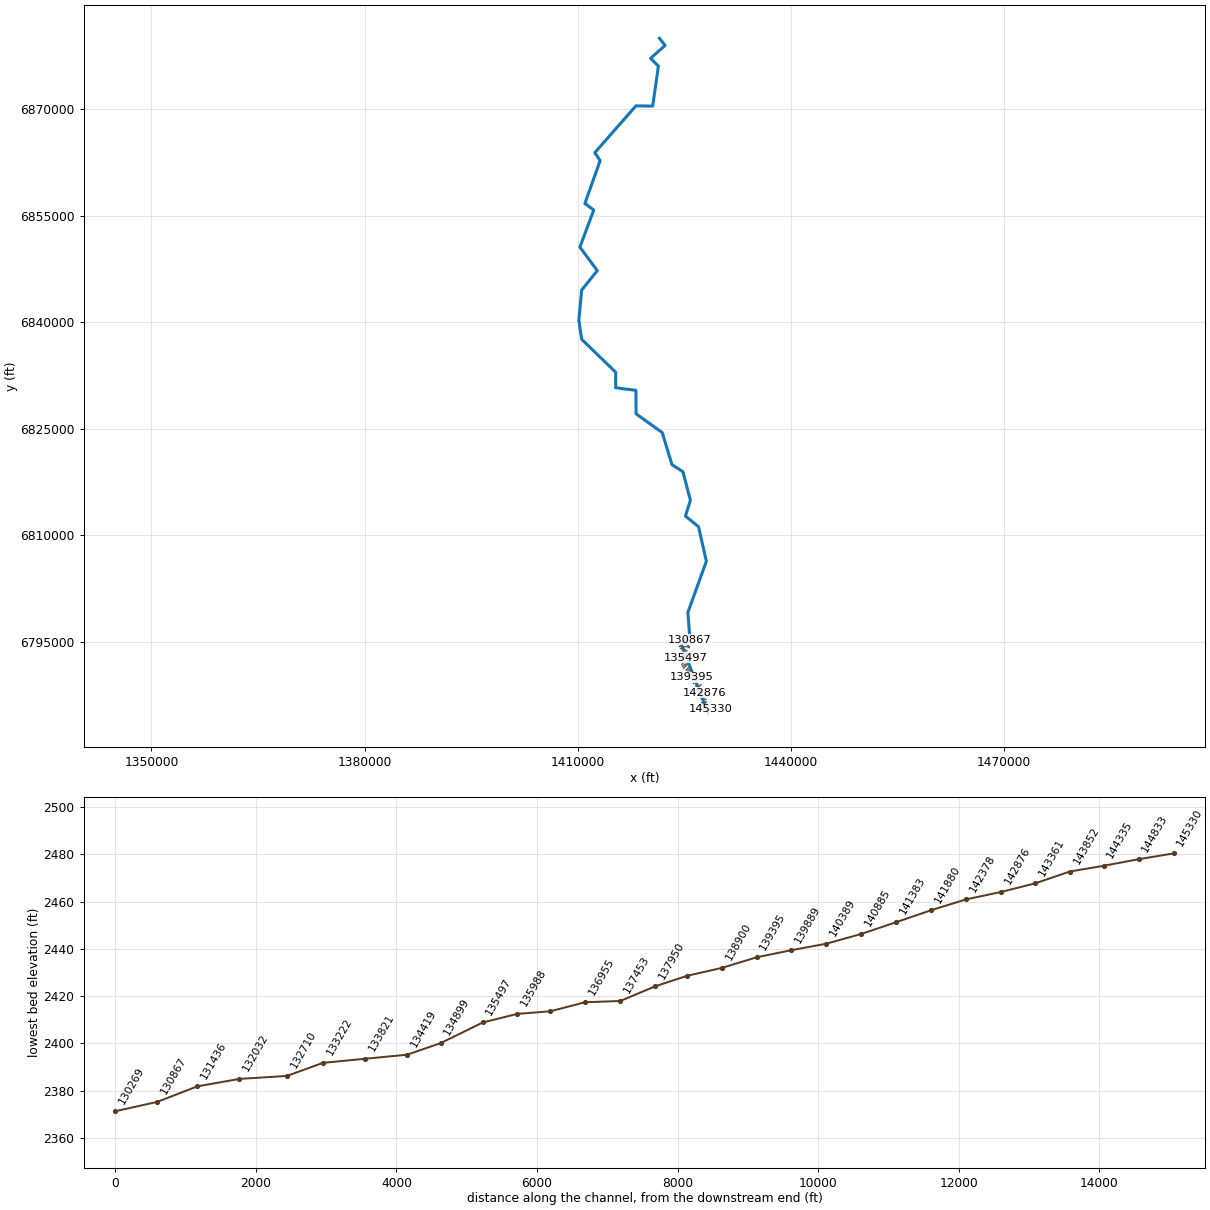
--- Bitter Creek.prj (project) ---

Proj Title=Bitter Creek Base Level Engineering
Current Plan=p01
Default Exp/Contr=0.3,0.1
English Units
Geom File=g01
Flow File=f01
Plan File=p01
Y Axis Title=Elevation
X Axis Title(PF)=Main Channel Distance
X Axis Title(XS)=Station
BEGIN DESCRIPTION:
Bitter Creek
END DESCRIPTION:
DSS Export Rating Curves= 0
DSS Export Rating Curve Sorted= 0
DSS Export Volume Flow Curves= 0
DXF OffsetX= 0
DXF OffsetY= 0
DXF ScaleX= 1
DXF ScaleY= 10

--- Bitter Creek.p01 (plan) ---

Plan Title=Multiple Run
Short Identifier=Multiple
Geom File=g01
Flow File=f01
Subcritical Flow
K Sum by GR= 0
Std Step Tol= 0.01
Critical Tol= 0.01
Num of Std Step Trials= 20
Max Error Tol= 0.3
Flow Tol Ratio= 0.001
Split Flow NTrial= 30
Split Flow Tol= 0.02
Split Flow Ratio= 0.02
Log Output Level= 0
Friction Slope Method= 1
Unsteady Friction Slope Method= 2
Unsteady Bridges Friction Slope Method= 1
Parabolic Critical Depth
Global Vel Dist=  1 , 1 , 1
Global Log Level= 0
CheckData=True
Encroach Param= -1, 0, 0, 0
BEGIN DESCRIPTION:
Multiple Run
END DESCRIPTION:

--- Bitter Creek.f01 (steady flow) ---

Flow Title=Multiple
Number of Profiles=7
Profile Names=10-year,25-year,50-year,1pct_min,100-year,1pct_plu,500-year
River Rch & RM= Bitter Creek,Reach-1,145330
     199     268     323     193     385     768     555
River Rch & RM= Bitter Creek,Reach-1,142876
     334     463     569     347     693    1383    1039
River Rch & RM= Bitter Creek,Reach-1,141880
     420     594     740     457     912    1820    1403
River Rch & RM= Bitter Creek,Reach-1,137453
     669     971    1231     773    1542    3078    2454
River Rch & RM= Bitter Creek,Reach-1,134899
    1715    2575    3338    2139    4267    8514    7064
River Rch & RM= Bitter Creek,Reach-1,127324
    1755    2639    3426    2198    4386    8751    7282
River Rch & RM= Bitter Creek,Reach-1,125533
    1870    2822    3670    2359    4707    9392    7844
River Rch & RM= Bitter Creek,Reach-1,123143
    1945    2939    3826    2462    4913    9802    8202
River Rch & RM= Bitter Creek,Reach-1,121991
    2061    3129    4087    2639    5266   10506    8851
River Rch & RM= Bitter Creek,Reach-1,116101
    2143    3260    4264    2757    5500   10974    9268
River Rch & RM= Bitter Creek,Reach-1,113726
    2143    3259    4262    2754    5496   10966    9257
River Rch & RM= Bitter Creek,Reach-1,113129
    2987    4593    6053    3941    7863   15688   13432
River Rch & RM= Bitter Creek,Reach-1,108990
    3055    4703    6202    4041    8062   16086   13793
River Rch & RM= Bitter Creek,Reach-1,105480
    2931    4525    5978    3901    7784   15530   13368
River Rch & RM= Bitter Creek,Reach-1,104282
    3225    4970    6562    4279    8537   17034   14632
River Rch & RM= Bitter Creek,Reach-1,96514
    3118    4821    6376    4165    8310   16581   14300
River Rch & RM= Bitter Creek,Reach-1,90361
    3141    4858    6426    4199    8377   16715   14422
River Rch & RM= Bitter Creek,Reach-1,88950
    4204    6553    8719    5726   11425   22795   19866
River Rch & RM= Bitter Creek,Reach-1,87656
    4837    7561   10081    6633   13234   26406   23095
River Rch & RM= Bitter Creek,Reach-1,81395
    4843    7569   10088    6636   13241   26420   23096
River Rch & RM= Bitter Creek,Reach-1,79352
    4866    7604   10135    6666   13301   26539   23197
River Rch & RM= Bitter Creek,Reach-1,77232
    4978    7782   10375    6826   13619   27173   23760
River Rch & RM= Bitter Creek,Reach-1,72759
    5001    7816   10419    6854   13675   27286   23854
River Rch & RM= Bitter Creek,Reach-1,70137
    5034    7868   10490    6901   13770   27474   24021
River Rch & RM= Bitter Creek,Reach-1,67943
    5342    8361   11157    7346   14658   29246   25612
River Rch & RM= Bitter Creek,Reach-1,64973
    5380    8417   11228    7391   14747   29424   25753
River Rch & RM= Bitter Creek,Reach-1,61436
    5378    8403   11200    7366   14698   29326   25621
River Rch & RM= Bitter Creek,Reach-1,54906
    5428    8483   11309    7438   14842   29613   25876
River Rch & RM= Bitter Creek,Reach-1,53911
    6088    9533   12728    8383   16727   33374   29238
River Rch & RM= Bitter Creek,Reach-1,51452
    6060    9482   12652    8329   16618   33157   29013
River Rch & RM= Bitter Creek,Reach-1,45218
    6005    9383   12508    8225   16412   32746   28596
River Rch & RM= Bitter Creek,Reach-1,42284
    5993    9352   12456    8184   16329   32582   28401
River Rch & RM= Bitter Creek,Reach-1,37344
    6161    9641   12865    8469   16898   33717   29505
River Rch & RM= Bitter Creek,Reach-1,35375
    6228    9745   13003    8560   17079   34077   29818
River Rch & RM= Bitter Creek,Reach-1,30589
    6256    9789   13063    8599   17157   34233   29954
River Rch & RM= Bitter Creek,Reach-1,27614
    6291    9845   13139    8649   17258   34434   30132
River Rch & RM= Bitter Creek,Reach-1,23212
    6265    9796   13064    8595   17149   34216   29902
River Rch & RM= Bitter Creek,Reach-1,13401
    6464   10107   13480    8868   17694   35305   30853
River Rch & RM= Bitter Creek,Reach-1,11275
    6488   10143   13528    8899   17756   35428   30957
River Rch & RM= Bitter Creek,Reach-1,9419
    6491   10146   13530    8900   17757   35430   30950
River Rch & RM= Bitter Creek,Reach-1,5474
    6403    9992   13308    8743   17445   34807   30332
River Rch & RM= Bitter Creek,Reach-1,1271
    6397    9981   13293    8732   17423   34764   30287
Boundary for River Rch & Prof#=Bitter Creek,Reach-1,1
Up Type=0
Dn Type=3
Dn Slope=0.005
Boundary for River Rch & Prof#=Bitter Creek,Reach-1,2
Up Type=0
Dn Type=3
Dn Slope=0.005
Boundary for River Rch & Prof#=Bitter Creek,Reach-1,3
Up Type=0
Dn Type=3
Dn Slope=0.005
Boundary for River Rch & Prof#=Bitter Creek,Reach-1,4
Up Type=0
Dn Type=3
Dn Slope=0.005
Boundary for River Rch & Prof#=Bitter Creek,Reach-1,5
Up Type=0
Dn Type=3
Dn Slope=0.005
Boundary for River Rch & Prof#=Bitter Creek,Reach-1,6
Up Type=0
Dn Type=3
Dn Slope=0.005
Boundary for River Rch & Prof#=Bitter Creek,Reach-1,7
Up Type=0
Dn Type=3
Dn Slope=0.005

--- Bitter Creek.g01 (geometry) ---

Geom Title=Existing Conditions

River Reach=Bitter Creek,Reach-1
Reach XY= 30
      1428355.00      6784888.00      1424504.83      6794803.22
      1425753.03      6795849.97      1425506.10      6799127.45
      1428105.55      6806312.87      1427002.42      6811179.53
      1425162.77      6812684.59      1425855.25      6814918.05
      1424802.95      6818932.16      1423260.71      6819935.41
      1421894.52      6824447.80      1418208.51      6827096.48
      1418194.52      6830397.80      1415331.48      6830760.99
      1415347.19      6832944.19      1410563.05      6837581.89
      1410154.85      6840262.87      1410558.53      6844536.53
      1412755.10      6847258.10      1410304.47      6850572.81
      1412253.95      6855798.43      1411004.50      6856712.96
      1413153.80      6862748.50      1412406.97      6863882.35
      1418194.49      6870477.52      1420549.55      6870435.55
      1421355.24      6876063.10      1420255.49      6877172.78
      1422302.00      6878989.40      1421505.00      6879988.00

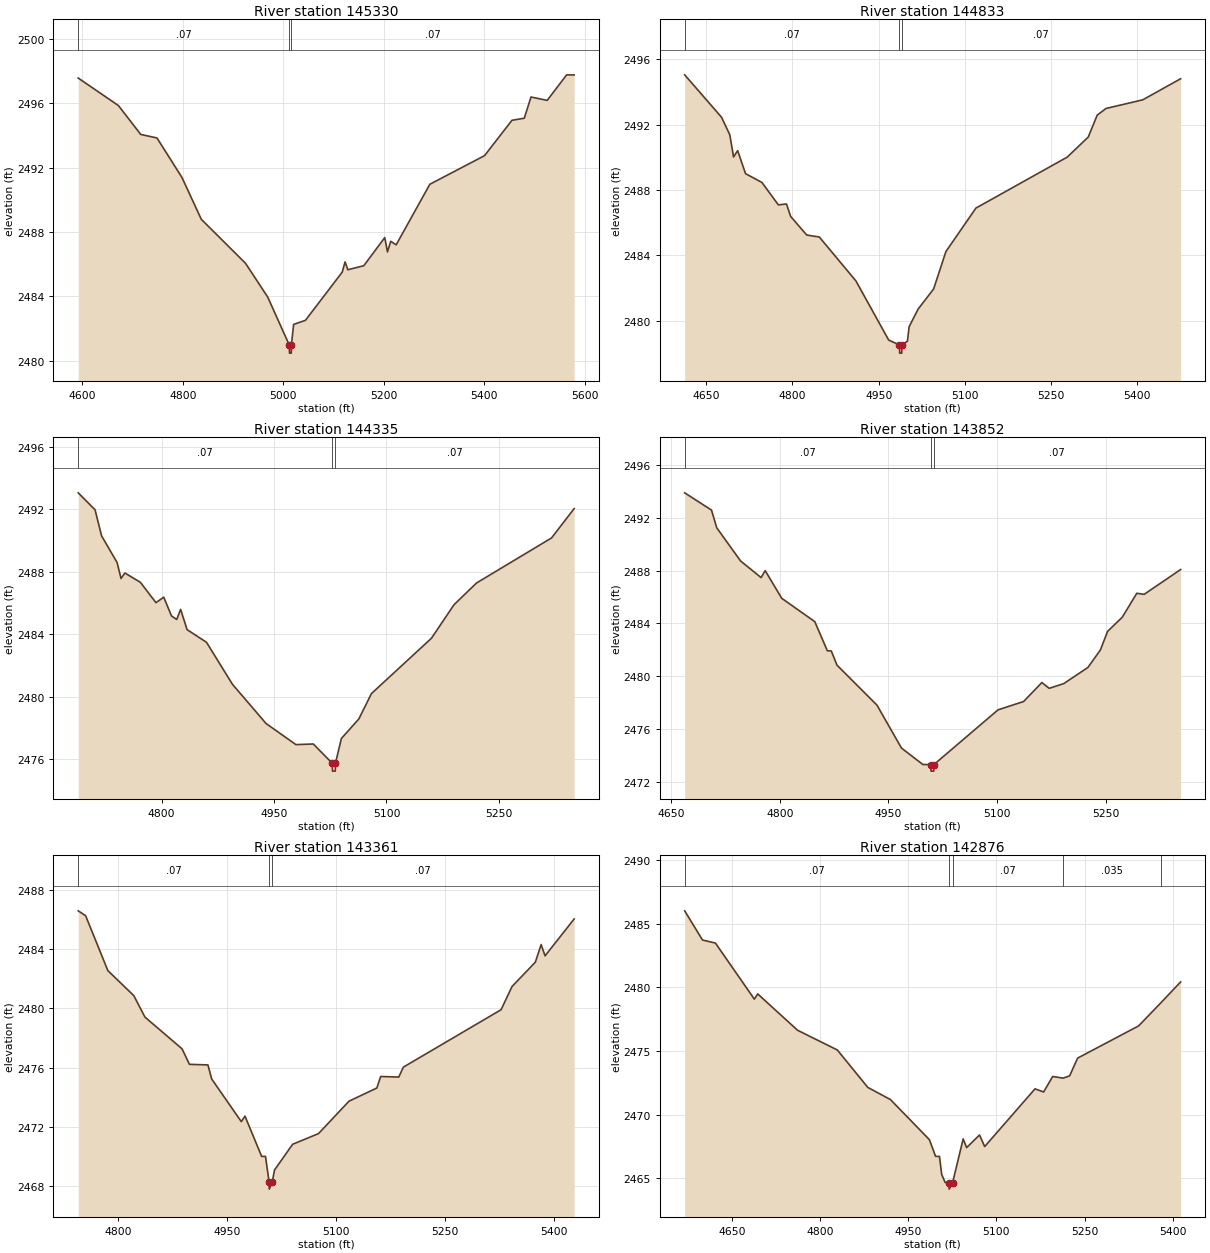
Type RM Length L Ch R = 1,145330,497,497,497
BEGIN DESCRIPTION:
Bitter Creek 171.0
END DESCRIPTION:
XS GIS Cut Line= 3
      1427755.01      6785038.01      1428115.79      6785228.33
      1428654.96      6785437.99
#Sta/Elev= 30
  4592.1 2497.58  4672.0 2495.87  4716.5 2494.07  4748.8 2493.85  4798.5 2491.39
  4836.9 2488.79  4924.9 2486.05  4969.0 2483.95  5012.0 2480.96  5012.3 2480.46
  5015.9 2480.46  5016.1 2480.96  5020.6 2482.25  5044.0 2482.50  5117.2 2485.50
  5122.9 2486.14  5128.3 2485.65  5160.1 2485.90  5201.8 2487.65  5207.2 2486.76
  5213.7 2487.42  5224.5 2487.20  5291.5 2490.97  5400.3 2492.75  5454.8 2494.95
  5479.3 2495.08  5492.7 2496.40  5524.9 2496.19  5563.6 2497.78  5578.5 2497.77
#Mann=3,-1,0
  4592.1    0.07       0  5012.0    0.07       0  5016.1    0.07       0
Bank Sta=5012,5016.1
Exp/Cntr=0.3,0.1

Type RM Length L Ch R = 1,144833,498,498,498
BEGIN DESCRIPTION:
Bitter Creek 170.0
END DESCRIPTION:
XS GIS Cut Line= 3
      1427705.01      6785438.00      1427999.23      6785690.32
      1428405.01      6785938.01
#Sta/Elev= 30
  4612.4 2495.06  4676.6 2492.46  4690.9 2491.39  4697.5 2490.03  4704.6 2490.42
  4718.3 2489.01  4746.8 2488.47  4775.4 2487.10  4789.6 2487.15  4796.8 2486.39
  4824.8 2485.25  4846.7 2485.13  4910.4 2482.44  4967.4 2478.82  4986.2 2478.52
  4986.5 2478.02  4990.1 2478.02  4990.3 2478.52  5000.0 2478.75  5003.0 2479.64
  5018.5 2480.71  5045.6 2481.95  5067.0 2484.24  5119.2 2486.90  5278.0 2490.02
  5314.7 2491.25  5330.2 2492.59  5345.6 2493.00  5409.6 2493.53  5475.4 2494.82
#Mann=3,-1,0
  4612.4    0.07       0  4986.2    0.07       0  4990.3    0.07       0
Bank Sta=4986.2,4990.3
Exp/Cntr=0.3,0.1

Type RM Length L Ch R = 1,144335,483,483,483
BEGIN DESCRIPTION:
Bitter Creek 169.0
END DESCRIPTION:
XS GIS Cut Line= 3
      1427604.95      6786037.99      1427905.21      6786119.80
      1428255.03      6786138.00
#Sta/Elev= 30
  4688.8 2493.06  4711.3 2491.97  4719.9 2490.31  4740.7 2488.59  4745.9 2487.57
  4751.1 2487.92  4771.8 2487.32  4792.5 2486.02  4802.9 2486.37  4813.2 2485.17
  4820.2 2484.94  4825.4 2485.59  4834.0 2484.29  4859.9 2483.48  4894.5 2480.79
  4939.4 2478.27  4979.2 2476.92  5002.4 2476.96  5027.7 2475.72  5028.0 2475.22
  5031.7 2475.22  5031.9 2475.72  5039.8 2477.31  5063.2 2478.57  5079.9 2480.19
  5160.0 2483.74  5190.1 2485.89  5220.1 2487.28  5320.2 2490.17  5350.3 2492.05
#Mann=3,-1,0
  4688.8    0.07       0  5027.7    0.07       0  5031.9    0.07       0
Bank Sta=5027.7,5031.9
Exp/Cntr=0.3,0.1

Type RM Length L Ch R = 1,143852,491,491,491
BEGIN DESCRIPTION:
Bitter Creek 168.0
END DESCRIPTION:
XS GIS Cut Line= 3
      1427454.96      6786387.98      1427754.55      6786528.72
      1428104.99      6786488.00
#Sta/Elev= 30
  4669.0 2493.90  4706.0 2492.59  4713.2 2491.25  4746.1 2488.73  4774.4 2487.47
  4780.0 2488.00  4802.8 2485.90  4848.4 2484.13  4865.7 2481.92  4871.2 2481.90
  4879.0 2480.83  4934.1 2477.80  4967.9 2474.54  4997.5 2473.29  5008.4 2473.29
  5008.7 2472.79  5012.4 2472.79  5012.7 2473.29  5101.1 2477.44  5136.3 2478.07
  5161.5 2479.51  5171.6 2479.07  5191.7 2479.43  5224.9 2480.65  5242.1 2481.97
  5252.1 2483.39  5272.3 2484.46  5292.4 2486.28  5302.5 2486.20  5352.8 2488.08
#Mann=3,-1,0
  4669.0    0.07       0  5008.4    0.07       0  5012.7    0.07       0
Bank Sta=5008.4,5012.7
Exp/Cntr=0.3,0.1

Type RM Length L Ch R = 1,143361,485,485,485
BEGIN DESCRIPTION:
Bitter Creek 167.0
END DESCRIPTION:
XS GIS Cut Line= 3
      1427405.00      6786938.00      1427654.85      6786988.00
      1428054.96      6786838.01
#Sta/Elev= 30
  4745.2 2486.59  4755.4 2486.26  4786.0 2482.55  4821.7 2480.86  4837.0 2479.41
  4888.0 2477.27  4898.2 2476.22  4923.6 2476.18  4928.8 2475.23  4969.5 2472.35
  4974.6 2472.72  4997.5 2470.00  5002.8 2470.00  5007.7 2468.29  5008.0 2467.79
  5012.1 2468.29  5015.2 2469.08  5040.1 2470.82  5075.7 2471.54  5117.6 2473.73
  5155.9 2474.62  5161.2 2475.40  5186.1 2475.36  5192.4 2476.03  5326.8 2479.91
  5341.9 2481.48  5373.9 2483.12  5381.9 2484.31  5387.3 2483.55  5427.3 2486.04
#Mann=3,-1,0
  4745.2    0.07       0  5007.7    0.07       0  5012.1    0.07       0
Bank Sta=5007.7,5012.1
Exp/Cntr=0.3,0.1

Type RM Length L Ch R = 1,142876,498,498,498
BEGIN DESCRIPTION:
Bitter Creek 166.0
END DESCRIPTION:
XS GIS Cut Line= 3
      1427305.01      6787238.00      1427686.04      6787437.50
      1427905.02      6787788.03
#Sta/Elev= 30
  4569.9 2486.00  4600.2 2483.71  4622.2 2483.47  4688.4 2479.07  4694.1 2479.48
  4761.8 2476.63  4829.5 2475.08  4881.4 2472.14  4919.8 2471.19  4986.1 2468.04
  4996.6 2466.73  5003.2 2466.73  5007.0 2465.31  5012.9 2464.68  5019.2 2464.66
  5019.7 2464.16  5025.5 2464.66  5043.5 2468.10  5049.4 2467.42  5071.3 2468.41
  5080.1 2467.50  5165.7 2472.03  5180.3 2471.78  5195.7 2473.00  5213.6 2472.87
  5224.6 2473.05  5238.1 2474.44  5341.9 2476.97  5380.5 2478.82  5413.3 2480.42
#Mann=5,-1,0
  4569.9    0.07       0  5019.2    0.07       0  5025.5    0.07       0
  5213.6   0.035       0  5380.5    0.07       0
Bank Sta=5019.2,5025.5
Exp/Cntr=0.3,0.1

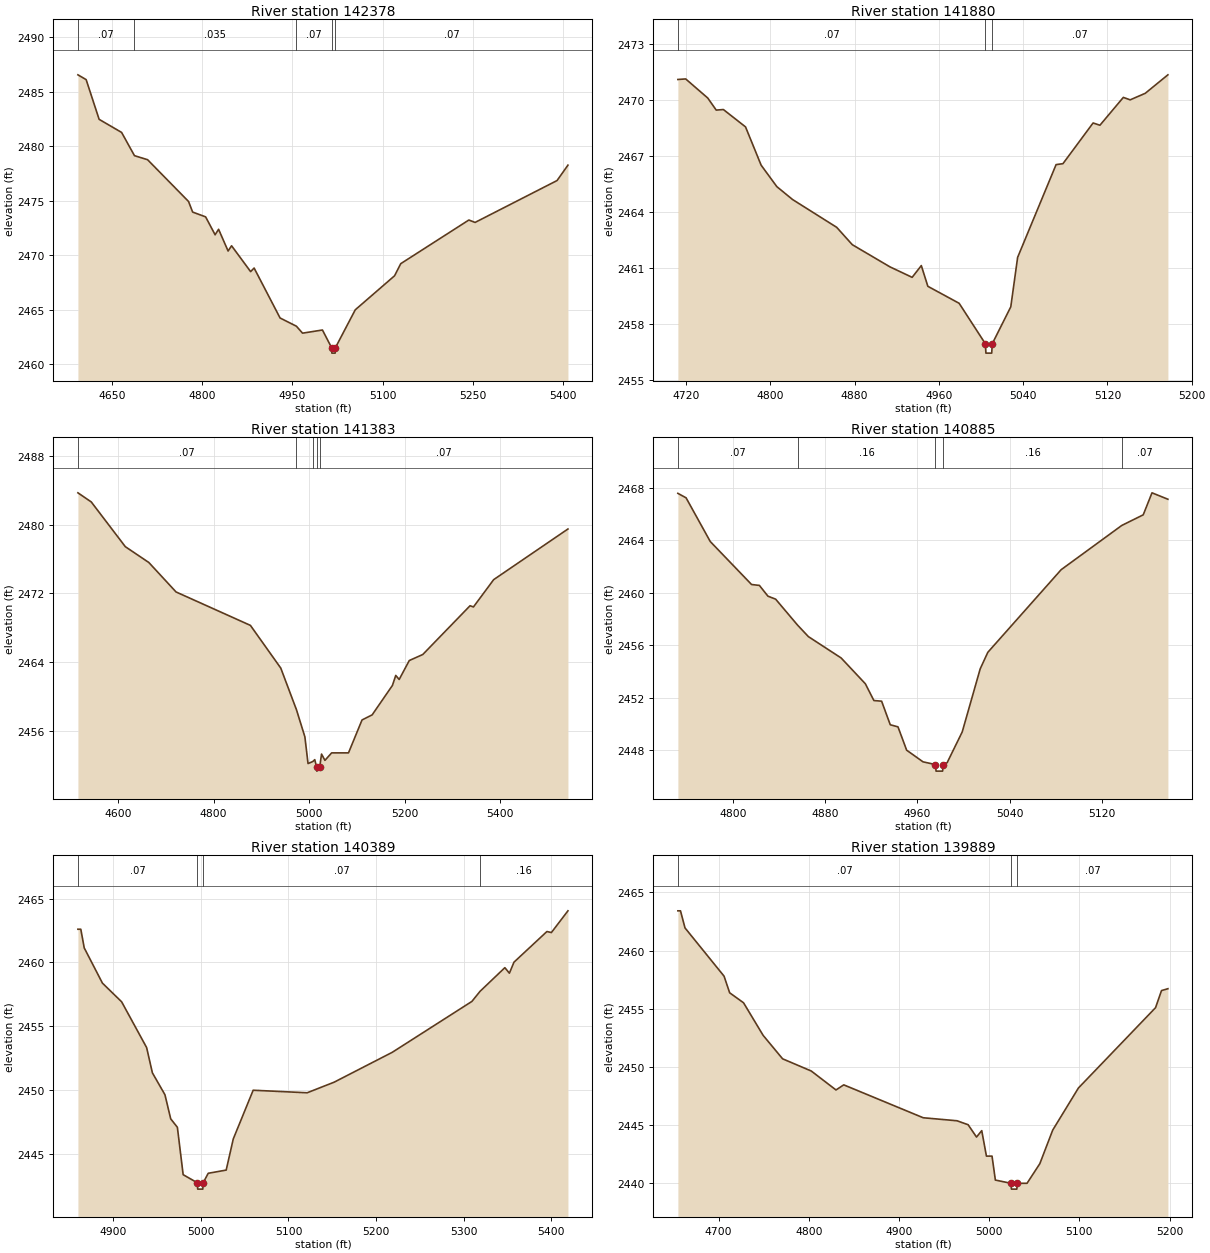
Type RM Length L Ch R = 1,142378,498,498,498
BEGIN DESCRIPTION:
Bitter Creek 165.0
END DESCRIPTION:
XS GIS Cut Line= 3
      1427005.02      6787588.01      1427358.55      6787789.47
      1427754.99      6787888.00
#Sta/Elev= 30
  4593.1 2486.53  4606.8 2486.09  4628.4 2482.45  4665.8 2481.25  4687.2 2479.12
  4709.0 2478.75  4777.2 2474.92  4784.0 2473.95  4805.6 2473.51  4821.4 2471.87
  4827.2 2472.37  4843.0 2470.38  4848.8 2470.86  4880.5 2468.49  4886.3 2468.82
  4929.5 2464.24  4956.6 2463.49  4966.9 2462.85  5000.0 2463.14  5015.2 2461.52
  5015.7 2461.02  5021.1 2461.02  5021.6 2461.52  5054.6 2464.99  5120.0 2468.11
  5130.3 2469.22  5243.6 2473.22  5254.0 2473.00  5390.4 2476.84  5408.5 2478.25
#Mann=5,-1,0
  4593.1    0.07       0  4687.2   0.035       0  4956.6    0.07       0
  5015.2    0.07       0  5021.6    0.07       0
Bank Sta=5015.2,5021.6
Exp/Cntr=0.3,0.1

Type RM Length L Ch R = 1,141880,497,497,497
BEGIN DESCRIPTION:
Bitter Creek 164.0
END DESCRIPTION:
XS GIS Cut Line= 3
      1427155.02      6788038.03      1427318.64      6788274.56
      1427455.01      6788388.01
#Sta/Elev= 30
  4712.4 2471.09  4719.8 2471.12  4740.7 2470.10  4748.8 2469.45  4755.6 2469.48
  4776.6 2468.55  4791.4 2466.50  4806.3 2465.35  4821.2 2464.66  4863.1 2463.17
  4877.9 2462.24  4913.7 2461.05  4934.7 2460.49  4943.4 2461.12  4949.6 2460.01
  4979.3 2459.10  5004.2 2456.93  5004.7 2456.43  5010.2 2456.43  5010.7 2456.93
  5028.3 2458.91  5034.8 2461.56  5071.3 2466.53  5077.8 2466.58  5106.4 2468.76
  5112.9 2468.64  5135.1 2470.13  5141.6 2470.00  5155.9 2470.35  5177.4 2471.34
#Mann=3,-1,0
  4712.4    0.07       0  5004.2    0.07       0  5010.7    0.07       0
Bank Sta=5004.2,5010.7
Exp/Cntr=0.3,0.1

Type RM Length L Ch R = 1,141383,498,498,498
BEGIN DESCRIPTION:
Bitter Creek 163.0
END DESCRIPTION:
XS GIS Cut Line= 3
      1426655.01      6788188.01      1426971.75      6788554.51
      1427355.02      6788938.02
#Sta/Elev= 30
  4515.6 2483.68  4543.6 2482.62  4614.9 2477.43  4664.2 2475.59  4721.2 2472.17
  4877.0 2468.29  4940.6 2463.33  4973.5 2458.49  4991.1 2455.35  4997.7 2452.25
  5007.6 2452.48  5011.8 2452.70  5015.6 2451.87  5016.1 2451.37  5022.2 2451.87
  5026.0 2453.35  5033.1 2452.62  5047.2 2453.49  5082.5 2453.49  5110.8 2457.31
  5132.0 2457.90  5174.5 2461.32  5181.5 2462.48  5188.6 2462.01  5209.8 2464.21
  5238.1 2464.91  5337.1 2470.57  5344.2 2470.43  5386.6 2473.60  5542.2 2479.48
#Mann=5,-1,0
  4515.6    0.07       0  4973.5   0.035       0  5007.6    0.07       0
  5015.6   0.035       0  5022.2    0.07       0
Bank Sta=5015.6,5022.2
Exp/Cntr=0.3,0.1

Type RM Length L Ch R = 1,140885,496,496,496
BEGIN DESCRIPTION:
Bitter Creek 162.0
END DESCRIPTION:
XS GIS Cut Line= 3
      1426604.97      6788737.97      1426771.66      6788921.33
      1426905.02      6789038.02
#Sta/Elev= 30
  4752.2 2467.59  4759.3 2467.25  4780.3 2463.91  4816.1 2460.63  4822.9 2460.56
  4830.3 2459.74  4837.0 2459.51  4856.0 2457.53  4865.4 2456.65  4893.8 2455.02
  4914.8 2453.05  4922.2 2451.77  4928.9 2451.72  4936.4 2449.92  4943.1 2449.76
  4950.6 2447.98  4964.8 2447.09  4975.6 2446.88  4976.1 2446.38  4981.8 2446.38
  4982.3 2446.88  4985.7 2447.02  4998.8 2449.37  5014.4 2454.19  5021.0 2455.45
  5084.6 2461.76  5137.2 2465.14  5155.8 2465.95  5163.4 2467.63  5177.2 2467.14
#Mann=5,-1,0
  4752.2    0.07       0  4856.0    0.16       0  4975.6    0.07       0
  4982.3    0.16       0  5137.2    0.07       0
Bank Sta=4975.6,4982.3
Exp/Cntr=0.3,0.1

Type RM Length L Ch R = 1,140389,500,500,500
BEGIN DESCRIPTION:
Bitter Creek 161.0
END DESCRIPTION:
XS GIS Cut Line= 3
      1426304.98      6789087.98      1426396.82      6789194.04
      1426805.04      6789288.01
#Sta/Elev= 30
  4859.7 2462.60  4863.0 2462.60  4866.9 2461.14  4887.7 2458.38  4909.6 2456.92
  4938.1 2453.34  4944.7 2451.36  4959.0 2449.65  4965.6 2447.76  4973.2 2447.10
  4979.8 2443.39  4995.9 2442.76  4996.4 2442.26  5002.2 2442.26  5002.7 2442.76
  5008.4 2443.50  5028.9 2443.75  5037.0 2446.19  5059.7 2450.00  5121.3 2449.80
  5152.1 2450.63  5218.5 2452.97  5309.3 2456.95  5318.6 2457.74  5346.9 2459.59
  5352.1 2459.16  5357.3 2460.02  5394.9 2462.42  5400.0 2462.34  5418.9 2464.04
#Mann=4,-1,0
  4859.7    0.07       0  4995.9    0.07       0  5002.7    0.07       0
  5318.6    0.16       0
Bank Sta=4995.9,5002.7
Exp/Cntr=0.3,0.1

Type RM Length L Ch R = 1,139889,494,494,494
BEGIN DESCRIPTION:
Bitter Creek 160.0
END DESCRIPTION:
XS GIS Cut Line= 3
      1426005.01      6789488.01      1426305.37      6789658.16
      1426454.99      6789787.99
#Sta/Elev= 30
  4654.8 2463.42  4657.7 2463.42  4662.7 2461.95  4706.0 2457.80  4712.2 2456.37
  4727.6 2455.51  4749.3 2452.71  4770.9 2450.69  4802.7 2449.64  4830.1 2448.01
  4838.7 2448.45  4926.8 2445.62  4964.3 2445.36  4976.6 2445.02  4985.9 2443.96
  4991.7 2444.51  4996.9 2442.32  5003.1 2442.32  5006.8 2440.26  5024.1 2439.98
  5024.6 2439.48  5030.6 2439.48  5031.1 2439.98  5041.9 2439.98  5056.1 2441.67
  5070.4 2444.56  5098.9 2448.18  5184.4 2455.09  5191.0 2456.56  5198.1 2456.72
#Mann=3,-1,0
  4654.8    0.07       0  5024.1    0.07       0  5031.1    0.07       0
Bank Sta=5024.1,5031.1
Exp/Cntr=0.3,0.1

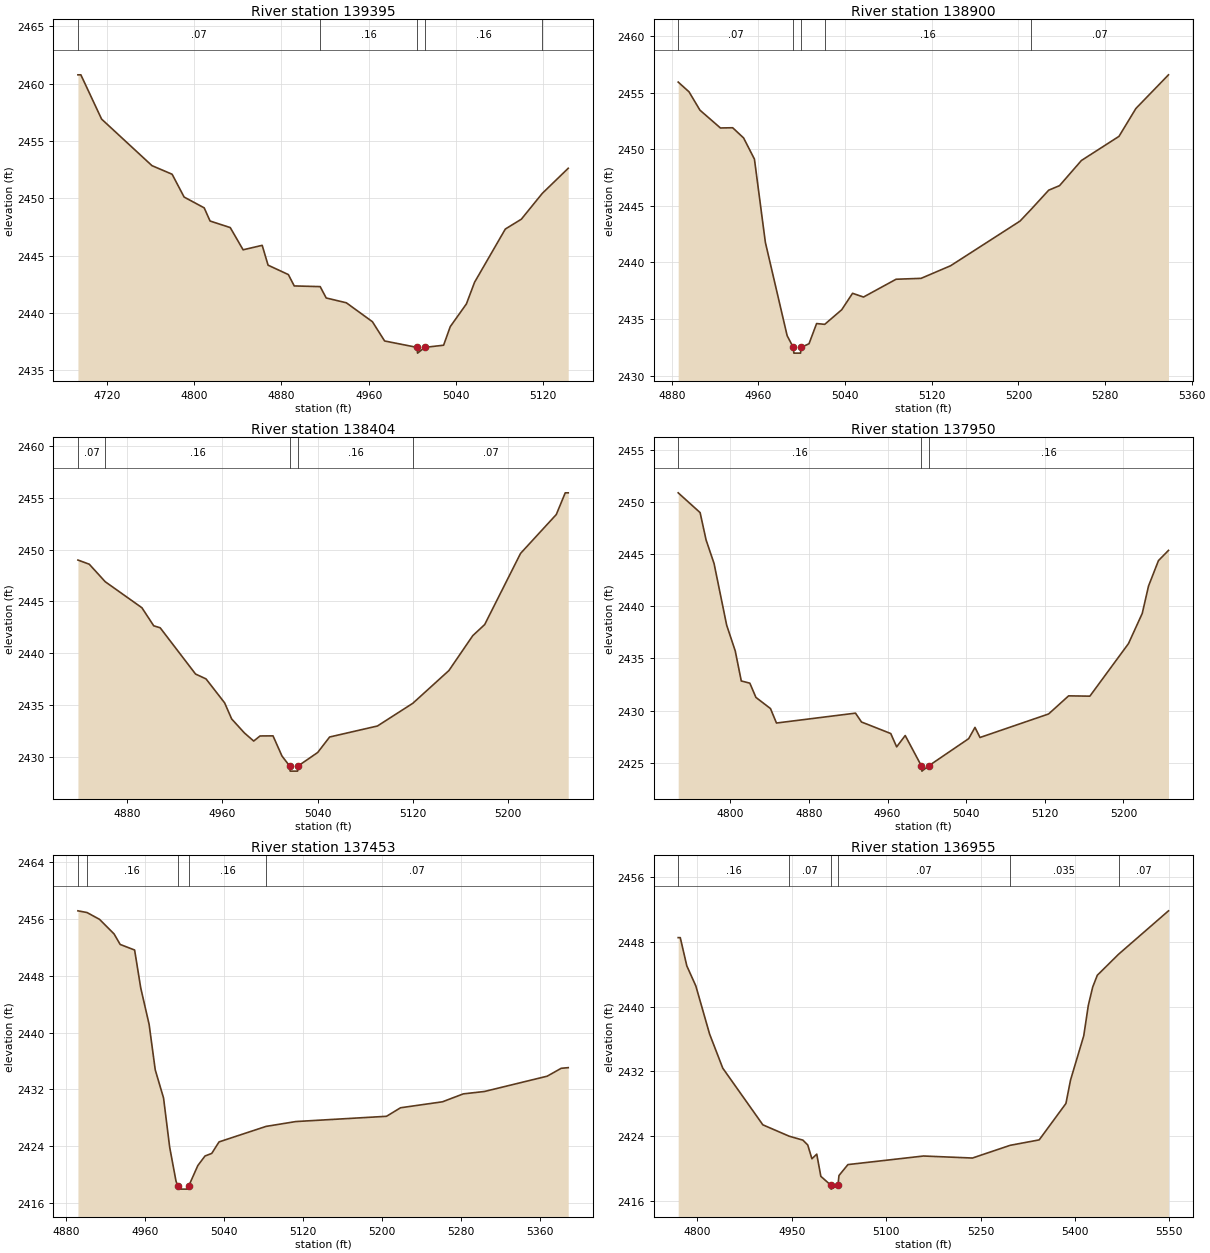
Type RM Length L Ch R = 1,139395,495,495,495
BEGIN DESCRIPTION:
Bitter Creek 159.0
END DESCRIPTION:
XS GIS Cut Line= 3
      1425654.98      6789787.99      1425938.48      6789905.02
      1426054.96      6789987.97
#Sta/Elev= 30
  4693.3 2460.76  4696.0 2460.76  4715.0 2456.90  4761.2 2452.84  4779.7 2452.09
  4790.7 2450.10  4809.1 2449.16  4814.5 2448.01  4833.0 2447.44  4844.8 2445.50
  4862.3 2445.89  4867.7 2444.16  4886.3 2443.34  4891.7 2442.35  4915.5 2442.29
  4921.0 2441.30  4939.5 2440.88  4963.4 2439.23  4974.6 2437.55  5004.3 2436.99
  5004.8 2436.49  5011.4 2436.99  5028.7 2437.18  5034.8 2438.80  5049.6 2440.78
  5057.1 2442.67  5085.3 2447.31  5100.0 2448.17  5119.2 2450.42  5143.0 2452.61
#Mann=5,-1,0
  4693.3    0.07       0  4915.5    0.16       0  5004.3    0.07       0
  5011.4    0.16       0  5119.2    0.07       0
Bank Sta=5004.3,5011.4
Exp/Cntr=0.3,0.1

Type RM Length L Ch R = 1,138900,496,496,496
BEGIN DESCRIPTION:
Bitter Creek 158.0
END DESCRIPTION:
XS GIS Cut Line= 3
      1425605.04      6790238.00      1425718.37      6790251.29
      1426054.97      6790288.00
#Sta/Elev= 30
  4885.9 2455.92  4895.9 2455.06  4906.0 2453.44  4924.9 2451.87  4936.2 2451.89
  4946.3 2450.99  4956.3 2449.12  4966.4 2441.77  4986.5 2433.54  4992.2 2432.50
  4992.7 2432.00  4998.9 2432.00  4999.4 2432.50  5006.7 2432.83  5013.7 2434.61
  5021.2 2434.54  5036.9 2435.83  5046.9 2437.28  5057.0 2436.95  5087.1 2438.52
  5110.2 2438.60  5137.4 2439.71  5201.5 2443.65  5211.5 2444.66  5228.0 2446.38
  5238.0 2446.78  5258.2 2449.00  5292.9 2451.13  5308.5 2453.59  5338.6 2456.56
#Mann=5,-1,0
  4885.9    0.07       0  4992.2    0.07       0  4999.4    0.07       0
  5021.2    0.16       0  5211.5    0.07       0
Bank Sta=4992.2,4999.4
Exp/Cntr=0.3,0.1

Type RM Length L Ch R = 1,138404,454,454,454
BEGIN DESCRIPTION:
Bitter Creek 157.0
END DESCRIPTION:
XS GIS Cut Line= 3
      1425605.03      6790638.01      1425754.88      6790697.14
      1426005.02      6790688.00
#Sta/Elev= 30
  4838.9 2448.99  4848.4 2448.59  4861.8 2446.90  4892.6 2444.39  4902.5 2442.65
  4907.9 2442.46  4937.6 2438.00  4946.4 2437.53  4962.0 2435.22  4967.9 2433.67
  4978.6 2432.32  4986.4 2431.54  4991.7 2432.03  5002.6 2432.04  5010.1 2430.10
  5016.5 2429.14  5017.0 2428.64  5023.2 2428.64  5023.7 2429.14  5040.1 2430.44
  5050.1 2431.93  5090.2 2432.99  5119.9 2435.18  5150.2 2438.34  5170.2 2441.70
  5180.2 2442.77  5210.3 2449.63  5240.3 2453.38  5247.8 2455.47  5250.3 2455.47
#Mann=5,-1,0
  4838.9    0.07       0  4861.8    0.16       0  5016.5    0.07       0
  5023.7    0.16       0  5119.9    0.07       0
Bank Sta=5016.5,5023.7
Exp/Cntr=0.3,0.1

Type RM Length L Ch R = 1,137950,497,497,497
BEGIN DESCRIPTION:
Bitter Creek 156.0
END DESCRIPTION:
XS GIS Cut Line= 3
      1425505.00      6790888.00      1425713.17      6791031.97
      1425955.00      6790988.00
#Sta/Elev= 30
  4746.9 2450.91  4769.2 2449.01  4775.3 2446.38  4783.4 2444.12  4796.2 2438.21
  4805.0 2435.71  4811.1 2432.84  4819.8 2432.63  4826.0 2431.26  4840.8 2430.19
  4846.9 2428.80  4927.3 2429.75  4933.4 2428.90  4963.2 2427.79  4969.2 2426.51
  4977.9 2427.60  4994.4 2424.68  4994.9 2424.18  5001.7 2424.68  5042.5 2427.30
  5048.9 2428.38  5054.0 2427.41  5123.8 2429.67  5144.2 2431.41  5165.8 2431.38
  5205.1 2436.43  5219.1 2439.33  5225.5 2441.96  5235.6 2444.40  5245.8 2445.38
#Mann=3,-1,0
  4746.9    0.16       0  4994.4    0.07       0  5001.7    0.16       0
Bank Sta=4994.4,5001.7
Exp/Cntr=0.3,0.1

Type RM Length L Ch R = 1,137453,498,498,498
BEGIN DESCRIPTION:
Bitter Creek 155.0
END DESCRIPTION:
XS GIS Cut Line= 3
      1425255.02      6790988.02      1425341.94      6791051.96
      1425604.99      6791337.99
#Sta/Elev= 30
  4892.1 2457.11  4901.3 2456.87  4914.0 2455.91  4928.7 2453.86  4934.9 2452.38
  4949.5 2451.60  4955.7 2446.27  4964.2 2441.14  4970.4 2434.74  4978.8 2430.80
  4985.0 2423.88  4991.4 2419.12  4993.0 2418.48  4993.5 2417.98  5004.0 2417.98
  5004.5 2418.48  5013.5 2421.29  5020.8 2422.64  5027.6 2423.00  5035.0 2424.62
  5082.6 2426.80  5112.7 2427.48  5204.6 2428.22  5218.8 2429.42  5261.3 2430.26
  5282.3 2431.37  5303.8 2431.71  5367.3 2433.86  5381.5 2434.97  5388.6 2435.06
#Mann=5,-1,0
  4892.1    0.07       0  4901.3    0.16       0  4993.0    0.07       0
  5004.5    0.16       0  5082.6    0.07       0
Bank Sta=4993,5004.5
Exp/Cntr=0.3,0.1

Type RM Length L Ch R = 1,136955,497,497,497
BEGIN DESCRIPTION:
Bitter Creek 154.0
END DESCRIPTION:
XS GIS Cut Line= 3
      1424905.00      6791238.00      1425054.71      6791412.88
      1425455.01      6791788.01
#Sta/Elev= 30
  4769.8 2448.53  4773.1 2448.53  4783.5 2445.04  4797.8 2442.57  4819.7 2436.62
  4840.6 2432.41  4904.3 2425.41  4946.0 2424.01  4967.9 2423.52  4975.6 2422.92
  4982.2 2421.22  4989.9 2421.79  4996.4 2419.05  5012.1 2417.97  5012.6 2417.47
  5023.6 2417.97  5025.2 2419.15  5039.4 2420.50  5159.5 2421.56  5237.2 2421.31
  5297.1 2422.88  5343.2 2423.55  5385.7 2428.05  5393.0 2430.94  5414.0 2436.41
  5421.3 2440.18  5428.2 2442.42  5435.5 2443.88  5469.2 2446.47  5548.6 2451.84
#Mann=6,-1,0
  4769.8    0.16       0  4946.0    0.07       0  5012.1    0.07       0
  5023.6    0.07       0  5297.1   0.035       0  5469.2    0.07       0
Bank Sta=5012.1,5023.6
Exp/Cntr=0.3,0.1

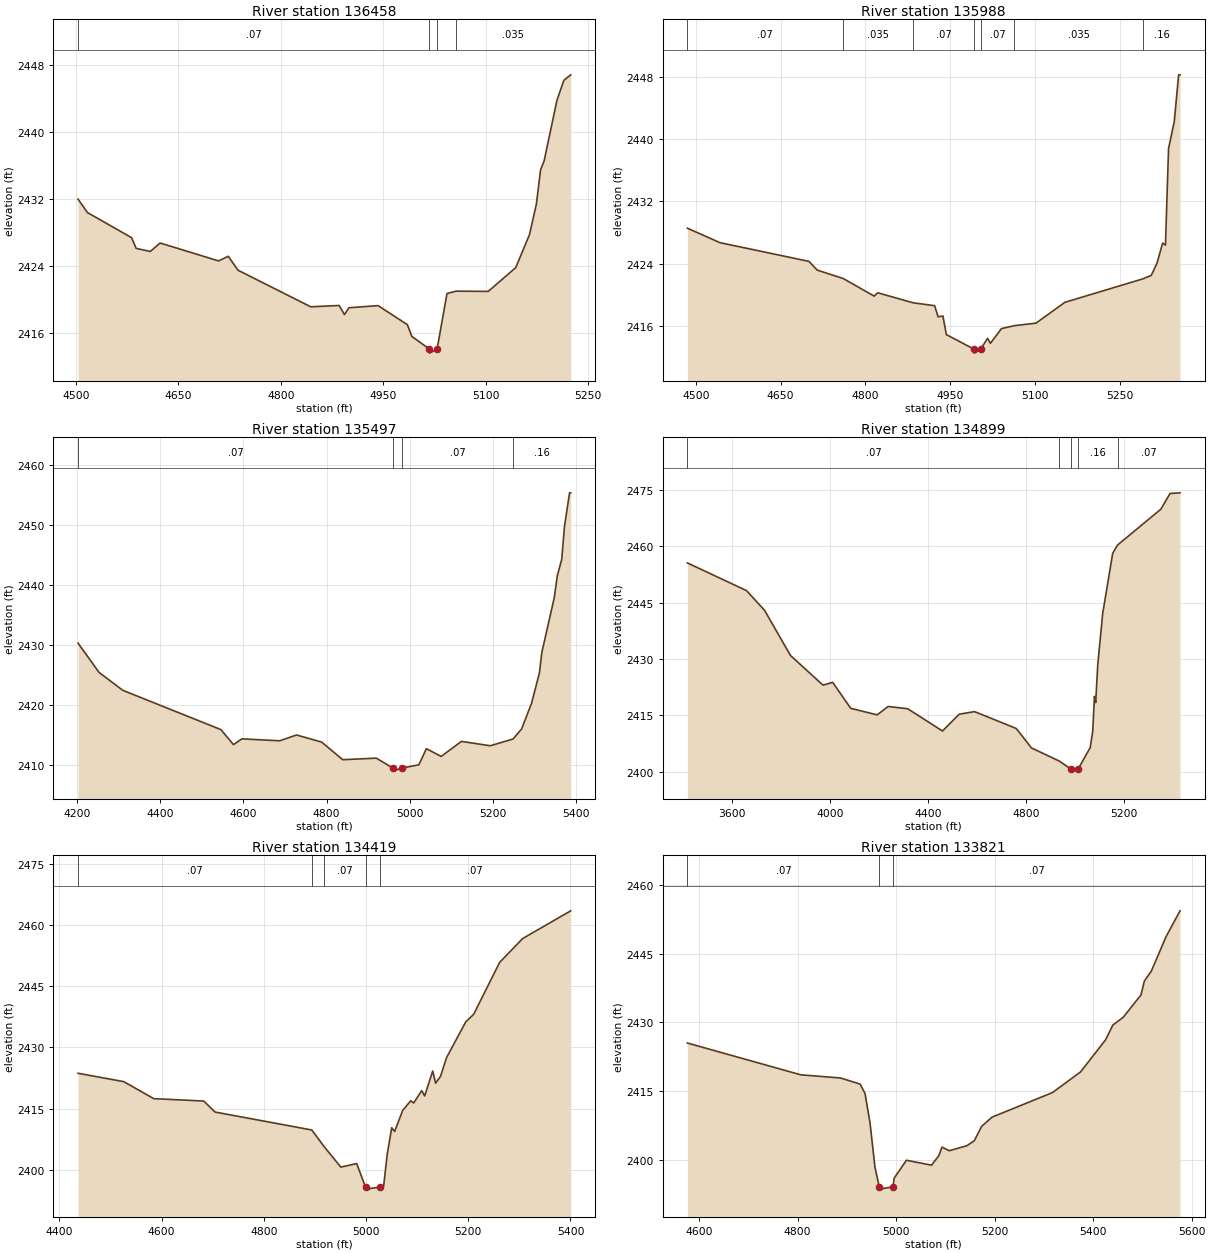
Type RM Length L Ch R = 1,136458,470,470,470
BEGIN DESCRIPTION:
Bitter Creek 153.0
END DESCRIPTION:
XS GIS Cut Line= 3
      1424754.98      6791487.99      1425132.00      6791811.82
      1425354.97      6791838.00
#Sta/Elev= 30
  4503.0 2432.01  4516.7 2430.41  4581.5 2427.40  4588.1 2426.13  4608.9 2425.76
  4623.2 2426.77  4708.8 2424.63  4723.0 2425.18  4737.3 2423.52  4843.8 2419.15
  4885.5 2419.31  4893.1 2418.22  4899.7 2419.04  4942.5 2419.29  4985.3 2417.02
  4991.9 2415.61  5017.4 2414.12  5017.9 2413.62  5028.9 2414.12  5043.3 2420.73
  5056.7 2421.02  5103.7 2420.99  5144.0 2423.83  5164.1 2427.76  5174.2 2431.40
  5180.4 2435.51  5185.5 2436.54  5204.4 2443.82  5214.5 2446.19  5224.5 2446.85
#Mann=4,-1,0
  4503.0    0.07       0  5017.4    0.07       0  5028.9    0.07       0
  5056.7   0.035       0
Bank Sta=5017.4,5028.9
Exp/Cntr=0.3,0.1

Type RM Length L Ch R = 1,135988,491,491,491
BEGIN DESCRIPTION:
Bitter Creek 152.0
END DESCRIPTION:
XS GIS Cut Line= 3
      1424655.00      6791738.00      1424955.16      6792156.25
      1425304.96      6792088.01
#Sta/Elev= 30
  4485.2 2428.57  4542.9 2426.71  4700.1 2424.31  4714.8 2423.19  4760.7 2422.11
  4815.5 2419.85  4821.7 2420.28  4884.5 2418.99  4922.4 2418.62  4928.5 2417.20
  4937.1 2417.29  4943.2 2414.91  4992.3 2413.03  4992.8 2412.53  5003.8 2413.03
  5016.0 2414.43  5021.1 2413.79  5040.6 2415.68  5063.0 2416.05  5101.7 2416.38
  5152.7 2419.05  5290.9 2422.07  5305.5 2422.51  5315.7 2424.09  5325.6 2426.65
  5330.6 2426.40  5336.1 2438.81  5346.2 2442.27  5353.9 2448.26  5356.4 2448.26
#Mann=7,-1,0
  4485.2    0.07       0  4760.7   0.035       0  4884.5    0.07       0
  4992.3    0.07       0  5003.8    0.07       0  5063.0   0.035       0
  5290.9    0.16       0
Bank Sta=4992.3,5003.8
Exp/Cntr=0.3,0.1

Type RM Length L Ch R = 1,135497,598,598,598
BEGIN DESCRIPTION:
Bitter Creek 151.0
END DESCRIPTION:
XS GIS Cut Line= 3
      1424005.02      6792488.00      1424794.52      6792597.80
      1425155.02      6792738.01
#Sta/Elev= 30
  4202.9 2430.29  4253.4 2425.40  4310.3 2422.41  4546.2 2415.84  4576.4 2413.33
  4596.6 2414.29  4687.5 2413.97  4727.9 2414.94  4788.5 2413.75  4838.9 2410.81
  4919.7 2411.07  4959.9 2409.40  4960.4 2408.90  4980.4 2409.40  5022.0 2409.96
  5040.0 2412.65  5075.6 2411.36  5124.3 2413.87  5193.6 2413.14  5248.3 2414.27
  5268.8 2415.94  5292.9 2420.27  5311.7 2425.35  5317.4 2428.71  5347.3 2437.89
  5354.6 2441.53  5365.3 2444.31  5371.8 2449.78  5384.1 2455.41  5386.8 2455.41
#Mann=4,-1,0
  4202.9    0.07       0  4959.9    0.07       0  4980.4    0.07       0
  5248.3    0.16       0
Bank Sta=4959.9,4980.4
Exp/Cntr=0.3,0.1

Type RM Length L Ch R = 1,134899,480,480,480
BEGIN DESCRIPTION:
Bitter Creek 150.0
END DESCRIPTION:
XS GIS Cut Line= 3
      1423605.00      6792388.00      1425035.08      6793067.97
      1425455.04      6792987.99
#Sta/Elev= 30
  3416.5 2455.55  3657.8 2448.18  3731.5 2442.95  3837.3 2430.93  3970.1 2423.04
  4009.6 2423.78  4083.3 2416.87  4191.3 2415.13  4235.9 2417.36  4316.0 2416.76
  4457.8 2410.84  4526.0 2415.30  4588.6 2416.00  4758.7 2411.52  4821.3 2406.33
  4934.7 2402.84  4983.3 2400.67  4983.8 2400.17  5011.1 2400.67  5061.0 2406.45
  5071.2 2410.82  5078.1 2420.05  5083.2 2418.41  5091.5 2428.36  5111.9 2442.15
  5152.6 2458.10  5172.7 2460.32  5349.2 2469.83  5386.7 2474.02  5427.5 2474.19
#Mann=5,-1,0
  3416.5    0.07       0  4934.7    0.16       0  4983.3    0.07       0
  5011.1    0.16       0  5172.7    0.07       0
Bank Sta=4983.3,5011.1
Exp/Cntr=0.3,0.1

Type RM Length L Ch R = 1,134419,598,598,598
BEGIN DESCRIPTION:
Bitter Creek 149.0
END DESCRIPTION:
XS GIS Cut Line= 3
      1424505.04      6793238.02      1425009.19      6793489.74
      1425355.04      6793287.98
#Sta/Elev= 30
  4436.5 2423.64  4525.9 2421.59  4584.7 2417.42  4682.4 2416.83  4704.7 2414.13
  4893.8 2409.74  4918.2 2405.63  4950.6 2400.64  4981.7 2401.50  4999.0 2395.74
  4999.5 2395.24  5026.9 2395.74  5034.4 2395.99  5041.5 2403.84  5050.2 2410.27
  5055.9 2409.38  5071.7 2414.54  5087.4 2416.89  5093.2 2416.36  5108.9 2419.37
  5114.7 2418.09  5130.4 2424.19  5136.2 2421.22  5145.7 2422.88  5157.7 2427.53
  5194.9 2436.20  5210.6 2438.11  5261.4 2450.82  5306.5 2456.67  5400.4 2463.46
#Mann=5,-1,0
  4436.5    0.07       0  4893.8    0.16       0  4918.2    0.07       0
  4999.0    0.07       0  5026.9    0.07       0
Bank Sta=4999,5026.9
Exp/Cntr=0.3,0.1

Type RM Length L Ch R = 1,133821,599,599,599
BEGIN DESCRIPTION:
Bitter Creek 148.0
END DESCRIPTION:
XS GIS Cut Line= 3
      1424454.96      6794038.00      1424877.84      6794011.58
      1425354.97      6793688.02
#Sta/Elev= 30
  4576.3 2425.49  4806.8 2418.53  4886.9 2417.85  4927.0 2416.51  4937.0 2414.44
  4947.1 2408.00  4957.1 2398.36  4965.8 2394.03  4966.3 2393.53  4993.7 2394.03
  4996.1 2395.93  5021.0 2399.85  5071.9 2398.77  5086.9 2400.86  5093.2 2402.72
  5107.9 2401.93  5143.8 2403.03  5158.8 2404.11  5173.7 2407.26  5194.7 2409.27
  5317.5 2414.65  5374.4 2419.16  5425.3 2426.18  5440.2 2429.43  5461.2 2431.13
  5497.2 2436.01  5504.0 2439.03  5518.2 2441.22  5548.1 2448.75  5576.5 2454.41
#Mann=3,-1,0
  4576.3    0.07       0  4965.8    0.07       0  4993.7    0.07       0
Bank Sta=4965.8,4993.7
Exp/Cntr=0.3,0.1

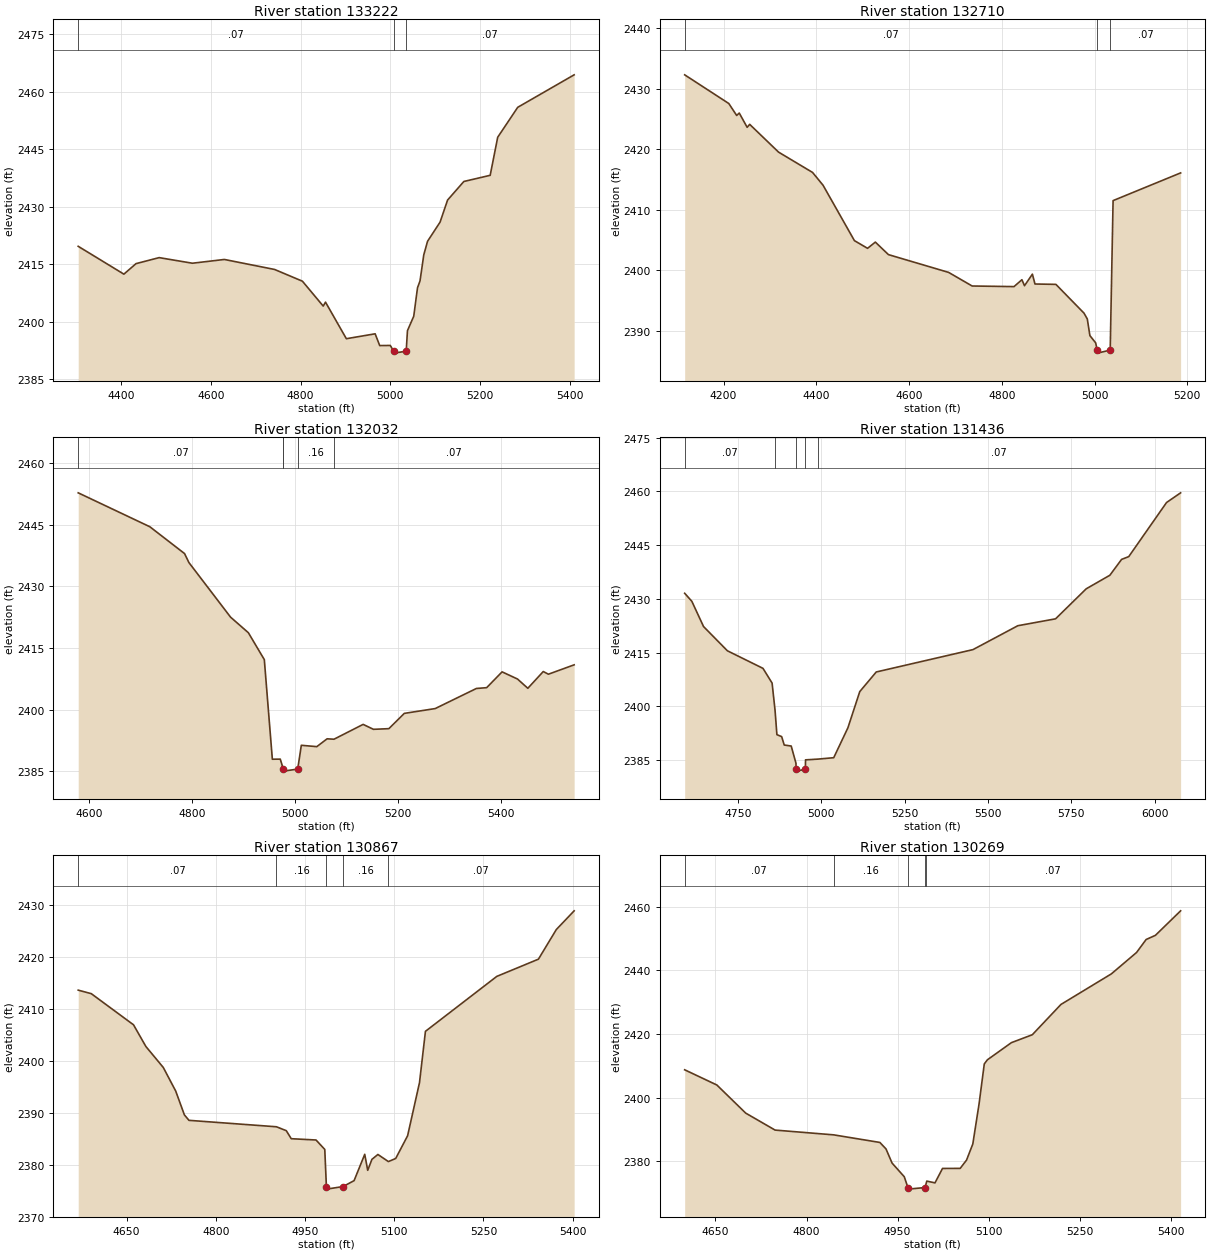
Type RM Length L Ch R = 1,133222,512,512,512
BEGIN DESCRIPTION:
Bitter Creek 147.0
END DESCRIPTION:
XS GIS Cut Line= 3
      1424655.00      6794188.00      1425338.20      6794321.39
      1425705.01      6794138.00
#Sta/Elev= 30
  4303.9 2419.66  4405.8 2412.40  4432.8 2415.14  4484.4 2416.71  4558.6 2415.25
  4629.9 2416.23  4742.0 2413.62  4804.0 2410.56  4850.4 2404.07  4855.5 2405.10
  4902.0 2395.56  4966.2 2396.84  4976.4 2393.77  5000.0 2393.80  5007.6 2392.30
  5008.1 2391.80  5035.5 2392.30  5038.3 2397.66  5052.3 2401.42  5060.7 2408.84
  5066.3 2410.64  5074.7 2417.43  5083.1 2420.97  5111.0 2425.96  5127.8 2431.73
  5164.1 2436.57  5222.8 2438.18  5239.6 2448.11  5284.3 2455.92  5410.1 2464.39
#Mann=3,-1,0
  4303.9    0.07       0  5007.6    0.07       0  5035.5    0.07       0
Bank Sta=5007.6,5035.5
Exp/Cntr=0.3,0.1

Type RM Length L Ch R = 1,132710,678,678,678
BEGIN DESCRIPTION:
Bitter Creek 4137
END DESCRIPTION:
XS GIS Cut Line= 3
      1424300.24      6794313.54      1425095.48      6794699.16
      1425279.43      6794723.06
#Sta/Elev= 30
  4116.2 2432.28  4211.3 2427.54  4228.3 2425.56  4233.9 2425.96  4250.9 2423.60
  4256.4 2424.09  4318.6 2419.50  4391.9 2416.14  4414.5 2414.03  4482.2 2404.86
  4510.5 2403.59  4527.3 2404.62  4555.5 2402.55  4685.3 2399.61  4736.0 2397.36
  4826.3 2397.26  4843.3 2398.40  4848.9 2397.41  4865.9 2399.32  4871.5 2397.69
  4916.6 2397.63  4977.2 2392.87  4984.3 2391.91  4989.9 2389.16  5002.3 2387.96
  5005.7 2386.76  5006.2 2386.26  5033.7 2386.76  5039.9 2411.48  5185.5 2416.06
#Mann=3,-1,0
  4116.2    0.07       0  5005.7    0.07       0  5033.7    0.07       0
Bank Sta=5005.7,5033.7
Exp/Cntr=0.3,0.1

Type RM Length L Ch R = 1,132032,596,596,596
BEGIN DESCRIPTION:
Bitter Creek 146.0
END DESCRIPTION:
XS GIS Cut Line= 3
      1424105.02      6794738.01      1424512.45      6794844.03
      1425055.02      6794838.00
#Sta/Elev= 30
  4579.0 2452.76  4718.2 2444.50  4785.6 2437.97  4794.1 2435.78  4875.1 2422.48
  4909.6 2418.70  4940.6 2412.15  4956.2 2387.90  4971.6 2387.92  4976.5 2385.91
  4977.5 2385.50  4978.0 2385.00  5005.5 2385.50  5012.5 2391.29  5042.6 2390.96
  5062.6 2392.87  5076.0 2392.77  5132.6 2396.38  5152.6 2395.18  5182.6 2395.34
  5212.6 2399.06  5272.6 2400.23  5352.6 2405.12  5372.6 2405.32  5402.6 2409.17
  5432.6 2407.42  5452.6 2405.17  5482.6 2409.25  5492.6 2408.60  5542.6 2410.88
#Mann=5,-1,0
  4579.0    0.07       0  4976.5    0.16       0  4977.5    0.07       0
  5005.5    0.16       0  5076.0    0.07       0
Bank Sta=4977.5,5005.5
Exp/Cntr=0.3,0.1

Type RM Length L Ch R = 1,131436,569,569,569
BEGIN DESCRIPTION:
Bitter Creek 145.0
END DESCRIPTION:
XS GIS Cut Line= 3
      1424705.00      6795388.00      1424968.23      6795074.31
      1425704.97      6794288.03
#Sta/Elev= 30
  4590.5 2431.55  4612.0 2429.30  4647.1 2422.25  4718.6 2415.48  4825.3 2410.57
  4852.6 2406.46  4861.4 2398.92  4867.0 2392.05  4881.3 2391.50  4889.0 2389.15
  4909.9 2388.87  4924.2 2384.06  4924.4 2382.36  4924.9 2381.86  4952.5 2382.36
  4952.8 2385.01  4989.2 2385.21  5037.4 2385.61  5079.9 2393.96  5115.5 2404.08
  5164.9 2409.56  5455.0 2415.81  5589.3 2422.48  5702.6 2424.41  5794.5 2432.80
  5865.3 2436.58  5900.5 2441.01  5922.0 2441.79  6035.3 2456.90  6077.5 2459.61
#Mann=5,-1,0
  4590.5    0.07       0  4861.4    0.16       0  4924.4    0.07       0
  4952.5    0.16       0  4989.2    0.07       0
Bank Sta=4924.4,4952.5
Exp/Cntr=0.3,0.1

Type RM Length L Ch R = 1,130867,598,598,598
BEGIN DESCRIPTION:
Bitter Creek 144.0
END DESCRIPTION:
XS GIS Cut Line= 3
      1425054.97      6795488.02      1425402.49      6795232.24
      1425805.05      6795238.00
#Sta/Elev= 30
  4568.5 2413.66  4590.5 2412.98  4661.5 2406.98  4682.3 2402.80  4711.6 2398.75
  4732.5 2394.20  4747.1 2389.61  4754.8 2388.56  4901.9 2387.32  4918.4 2386.57
  4926.8 2385.02  4968.5 2384.77  4983.2 2382.95  4985.9 2375.80  4986.4 2375.30
  5014.1 2375.80  5032.5 2376.94  5050.4 2382.01  5055.4 2378.93  5062.5 2381.04
  5072.5 2381.98  5090.2 2380.61  5102.5 2381.21  5122.5 2385.59  5142.5 2395.83
  5152.5 2405.72  5272.5 2416.31  5342.5 2419.63  5372.6 2425.34  5402.6 2428.95
#Mann=5,-1,0
  4568.5    0.07       0  4901.9    0.16       0  4985.9    0.07       0
  5014.1    0.16       0  5090.2    0.07       0
Bank Sta=4985.9,5014.1
Exp/Cntr=0.3,0.1

Type RM Length L Ch R = 1,130269,598,598,598
BEGIN DESCRIPTION:
Bitter Creek 143.0
END DESCRIPTION:
XS GIS Cut Line= 3
      1425305.03      6795738.00      1425703.78      6795698.51
      1426105.04      6795587.99
#Sta/Elev= 30
  4599.3 2408.77  4652.3 2404.00  4699.8 2395.18  4748.2 2389.85  4844.8 2388.35
  4920.8 2385.97  4930.9 2383.94  4940.9 2379.50  4961.0 2375.21  4967.0 2371.82
  4967.5 2371.32  4995.3 2371.82  4996.7 2372.83  4998.1 2373.84  5011.6 2373.28
  5024.0 2377.81  5053.1 2377.83  5063.6 2380.44  5073.9 2385.48  5084.2 2398.06
  5092.8 2410.60  5097.9 2411.90  5137.5 2417.29  5171.9 2419.77  5219.1 2429.28
  5302.1 2438.87  5343.6 2445.58  5359.4 2449.66  5374.7 2450.97  5416.2 2458.66
#Mann=5,-1,0
  4599.3    0.07       0  4844.8    0.16       0  4967.0    0.07       0
  4995.3    0.16       0  4996.7    0.07       0
Bank Sta=4967,4995.3
Exp/Cntr=0.3,0.1