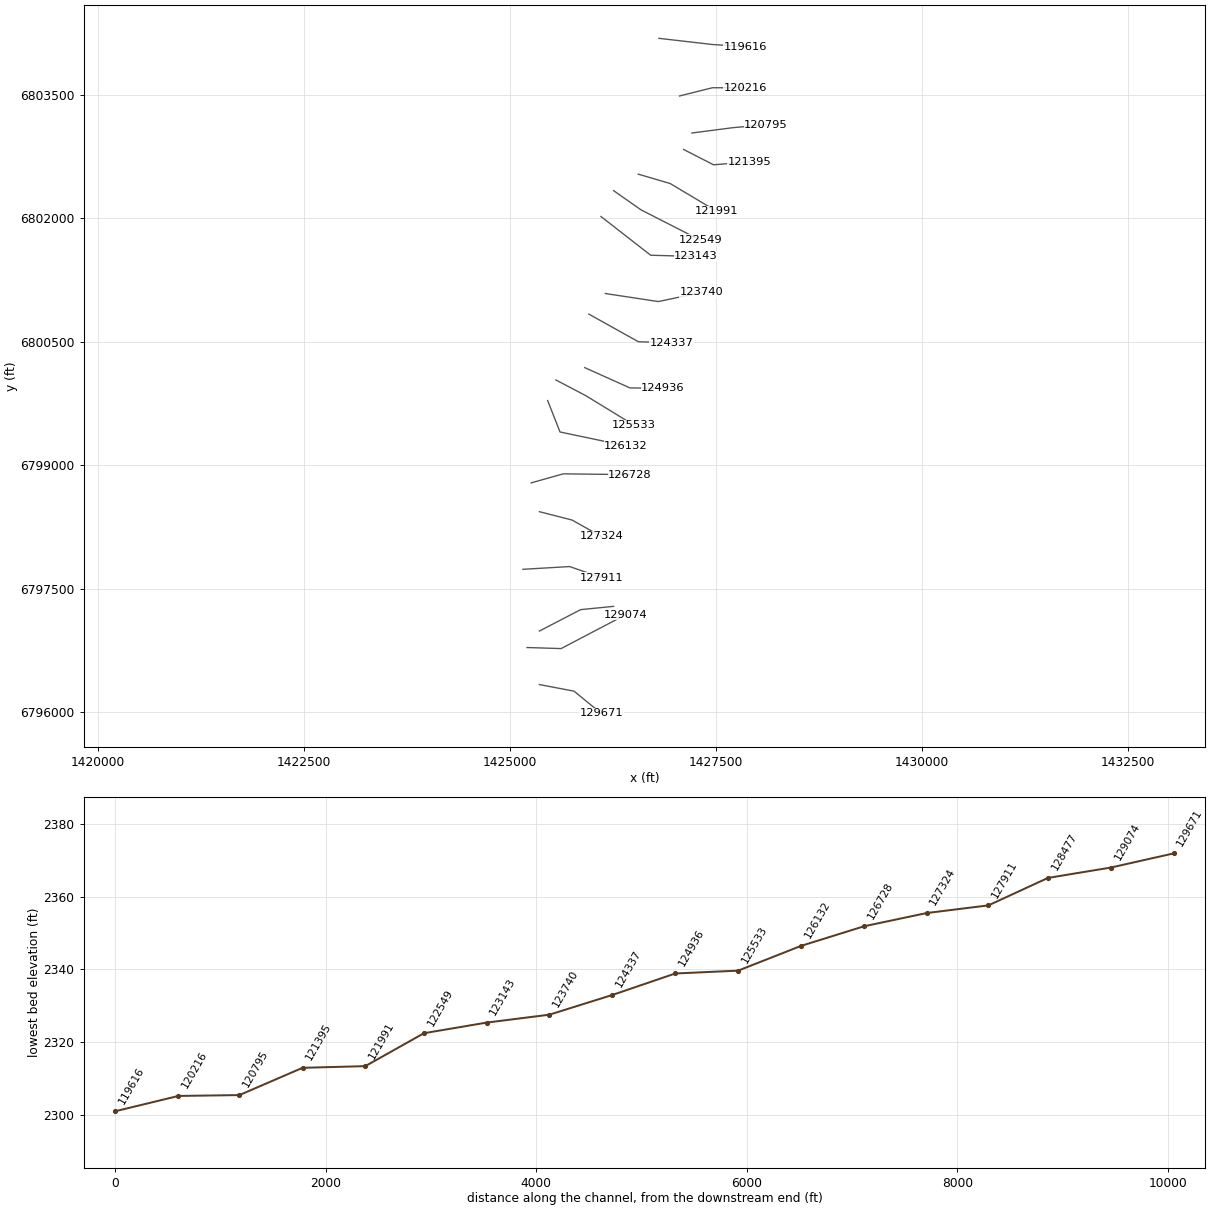
HEC-RAS study Bitter Creek.prj: Bitter Creek Base Level Engineering

--- Bitter Creek.g01 (geometry) --- (continued)

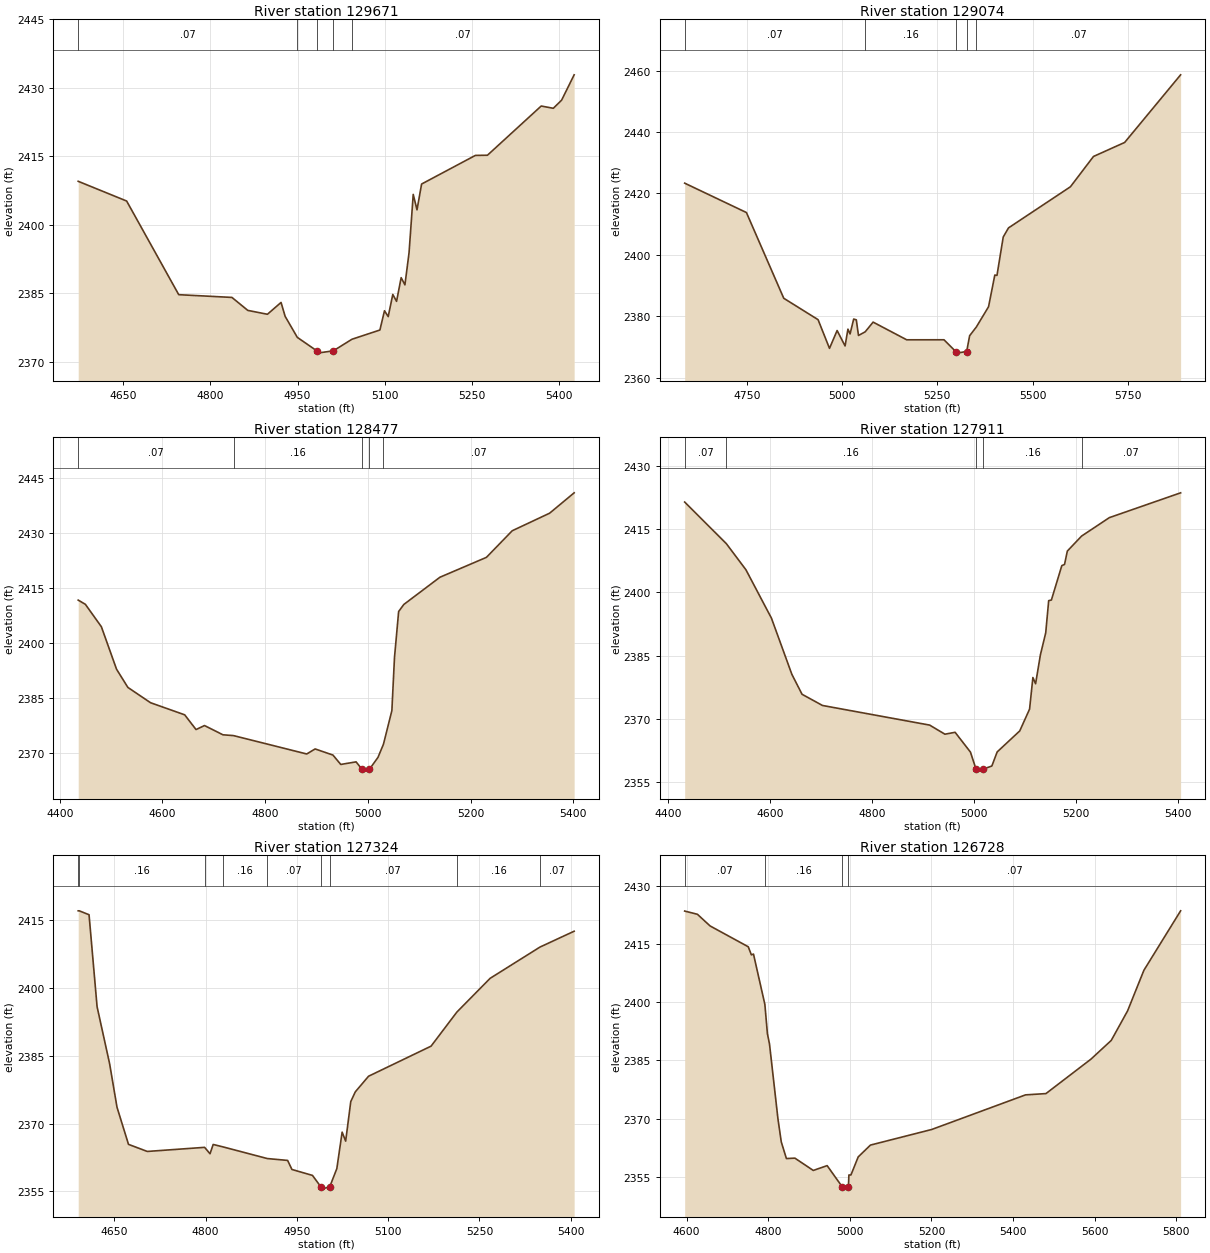
Type RM Length L Ch R = 1,129671,597,597,597
BEGIN DESCRIPTION:
Bitter Creek 142.0
END DESCRIPTION:
XS GIS Cut Line= 3
      1425354.95      6796338.01      1425775.10      6796257.96
      1426105.02      6795987.99
#Sta/Elev= 30
  4572.3 2409.49  4655.7 2405.17  4745.4 2384.66  4837.0 2384.06  4864.3 2381.22
  4898.1 2380.37  4921.6 2382.96  4928.6 2379.92  4949.6 2375.31  4983.2 2372.36
  4983.7 2371.86  5011.6 2372.36  5043.7 2374.90  5091.8 2376.92  5099.7 2381.14
  5106.1 2379.86  5114.0 2384.71  5120.5 2383.20  5128.4 2388.39  5134.9 2386.81
  5142.0 2393.85  5149.2 2406.62  5155.7 2403.24  5163.6 2408.89  5256.2 2415.16
  5277.0 2415.20  5369.6 2425.98  5390.4 2425.48  5404.7 2427.26  5426.3 2432.81
#Mann=5,-1,0
  4572.3    0.07       0  4949.6    0.16       0  4983.2    0.07       0
  5011.6    0.16       0  5043.7    0.07       0
Bank Sta=4983.2,5011.6
Exp/Cntr=0.3,0.1

Type RM Length L Ch R = 1,129074,597,597,597
BEGIN DESCRIPTION:
Bitter Creek 141.0
END DESCRIPTION:
XS GIS Cut Line= 3
      1425205.02      6796788.00      1425618.02      6796775.02
      1426405.03      6797188.02
#Sta/Elev= 30
  4586.8 2423.34  4748.9 2413.77  4846.9 2385.84  4937.0 2378.87  4967.0 2369.52
  4987.0 2375.33  5007.9 2370.31  5015.4 2375.77  5021.0 2374.22  5030.5 2379.07
  5037.4 2378.81  5043.1 2373.72  5060.8 2374.92  5081.5 2378.07  5169.7 2372.31
  5267.6 2372.32  5298.6 2368.47  5299.1 2367.97  5327.1 2368.47  5334.9 2373.64
  5352.5 2376.48  5384.6 2383.09  5401.0 2393.40  5406.7 2393.30  5423.1 2405.80
  5437.0 2408.77  5599.5 2422.16  5660.0 2432.03  5741.9 2436.60  5888.8 2458.63
#Mann=5,-1,0
  4586.8    0.07       0  5060.8    0.16       0  5298.6    0.07       0
  5327.1    0.16       0  5352.5    0.07       0
Bank Sta=5298.6,5327.1
Exp/Cntr=0.3,0.1

Type RM Length L Ch R = 1,128477,566,566,566
BEGIN DESCRIPTION:
Bitter Creek 140.0
END DESCRIPTION:
XS GIS Cut Line= 3
      1425354.96      6796987.98      1425855.46      6797248.19
      1426254.98      6797288.00
#Sta/Elev= 30
  4435.9 2411.68  4449.8 2410.54  4481.0 2404.43  4510.5 2392.88  4532.6 2387.91
  4576.8 2383.74  4643.2 2380.45  4665.3 2376.44  4681.8 2377.53  4717.7 2375.01
  4738.3 2374.79  4880.8 2369.79  4897.2 2371.16  4931.9 2369.49  4947.1 2366.94
  4976.9 2367.64  4988.5 2365.62  4988.7 2365.12  5002.9 2365.62  5019.6 2368.87
  5030.2 2372.44  5046.6 2381.59  5051.7 2396.07  5059.8 2408.58  5069.9 2410.50
  5140.2 2417.91  5230.7 2423.32  5280.9 2430.56  5353.7 2435.34  5401.5 2440.89
#Mann=5,-1,0
  4435.9    0.07       0  4738.3    0.16       0  4988.5    0.07       0
  5002.9    0.16       0  5030.2    0.07       0
Bank Sta=4988.5,5002.9
Exp/Cntr=0.3,0.1

Type RM Length L Ch R = 1,127911,587,587,587
BEGIN DESCRIPTION:
Bitter Creek 139.0
END DESCRIPTION:
XS GIS Cut Line= 3
      1425154.98      6797738.00      1425721.89      6797771.43
      1426105.02      6797637.99
#Sta/Elev= 30
  4432.1 2421.46  4513.9 2411.58  4552.3 2405.39  4602.4 2393.90  4642.5 2380.56
  4662.5 2375.82  4702.6 2373.16  4913.0 2368.50  4943.0 2366.34  4963.0 2366.79
  4993.1 2362.09  5004.0 2358.07  5004.2 2357.57  5018.5 2358.07  5035.1 2358.78
  5045.6 2362.13  5089.9 2367.12  5109.2 2372.30  5115.7 2379.79  5121.0 2378.32
  5130.4 2385.16  5140.9 2390.42  5146.7 2398.05  5152.0 2398.19  5172.5 2406.37
  5177.8 2406.64  5183.3 2409.82  5211.3 2413.38  5265.8 2417.76  5405.7 2423.65
#Mann=5,-1,0
  4432.1    0.07       0  4513.9    0.16       0  5004.0    0.07       0
  5018.5    0.16       0  5211.3    0.07       0
Bank Sta=5004,5018.5
Exp/Cntr=0.3,0.1

Type RM Length L Ch R = 1,127324,596,596,596
BEGIN DESCRIPTION:
Bitter Creek 138.0
END DESCRIPTION:
XS GIS Cut Line= 3
      1425355.01      6798438.00      1425751.30      6798336.40
      1426104.96      6798138.02
#Sta/Elev= 30
  4590.9 2417.14  4592.6 2417.14  4608.7 2416.27  4621.9 2395.89  4642.5 2383.25
  4654.6 2373.62  4673.5 2365.38  4704.4 2363.81  4798.5 2364.72  4807.4 2363.30
  4812.6 2365.36  4828.8 2364.82  4901.4 2362.24  4934.9 2361.82  4941.9 2359.82
  4975.7 2358.50  4989.5 2355.96  4989.8 2355.46  5004.0 2355.96  5015.7 2360.01
  5024.4 2368.09  5030.2 2366.10  5038.6 2374.87  5046.1 2377.03  5067.8 2380.48
  5170.5 2387.15  5212.8 2394.69  5267.5 2402.18  5349.4 2409.11  5405.5 2412.62
#Mann=9,-1,0
  4590.9    0.07       0  4592.6    0.16       0  4798.5    0.07       0
  4828.8    0.16       0  4901.4    0.07       0  4989.5    0.07       0
  5004.0    0.07       0  5212.8    0.16       0  5349.4    0.07       0
Bank Sta=4989.5,5004
Exp/Cntr=0.3,0.1

Type RM Length L Ch R = 1,126728,596,596,596
BEGIN DESCRIPTION:
Bitter Creek 137.0
END DESCRIPTION:
XS GIS Cut Line= 3
      1425255.00      6798788.00      1425644.52      6798897.80
      1426454.96      6798888.00
#Sta/Elev= 30
  4595.3 2423.53  4626.5 2422.70  4657.6 2419.69  4751.1 2414.32  4758.7 2412.24
  4763.9 2412.43  4791.8 2399.46  4798.0 2391.92  4803.1 2389.28  4823.9 2369.89
  4832.0 2363.98  4844.6 2359.69  4865.4 2359.80  4910.4 2356.63  4944.4 2357.87
  4982.0 2352.31  4982.2 2351.81  4996.5 2352.31  4997.7 2355.46  5002.7 2355.46
  5020.5 2360.12  5050.5 2363.17  5200.5 2367.19  5430.5 2376.12  5480.5 2376.45
  5590.5 2385.31  5640.5 2390.16  5680.5 2397.77  5720.5 2408.25  5810.5 2423.59
#Mann=4,-1,0
  4595.3    0.07       0  4791.8    0.16       0  4982.0    0.07       0
  4996.5    0.07       0
Bank Sta=4982,4996.5
Exp/Cntr=0.3,0.1

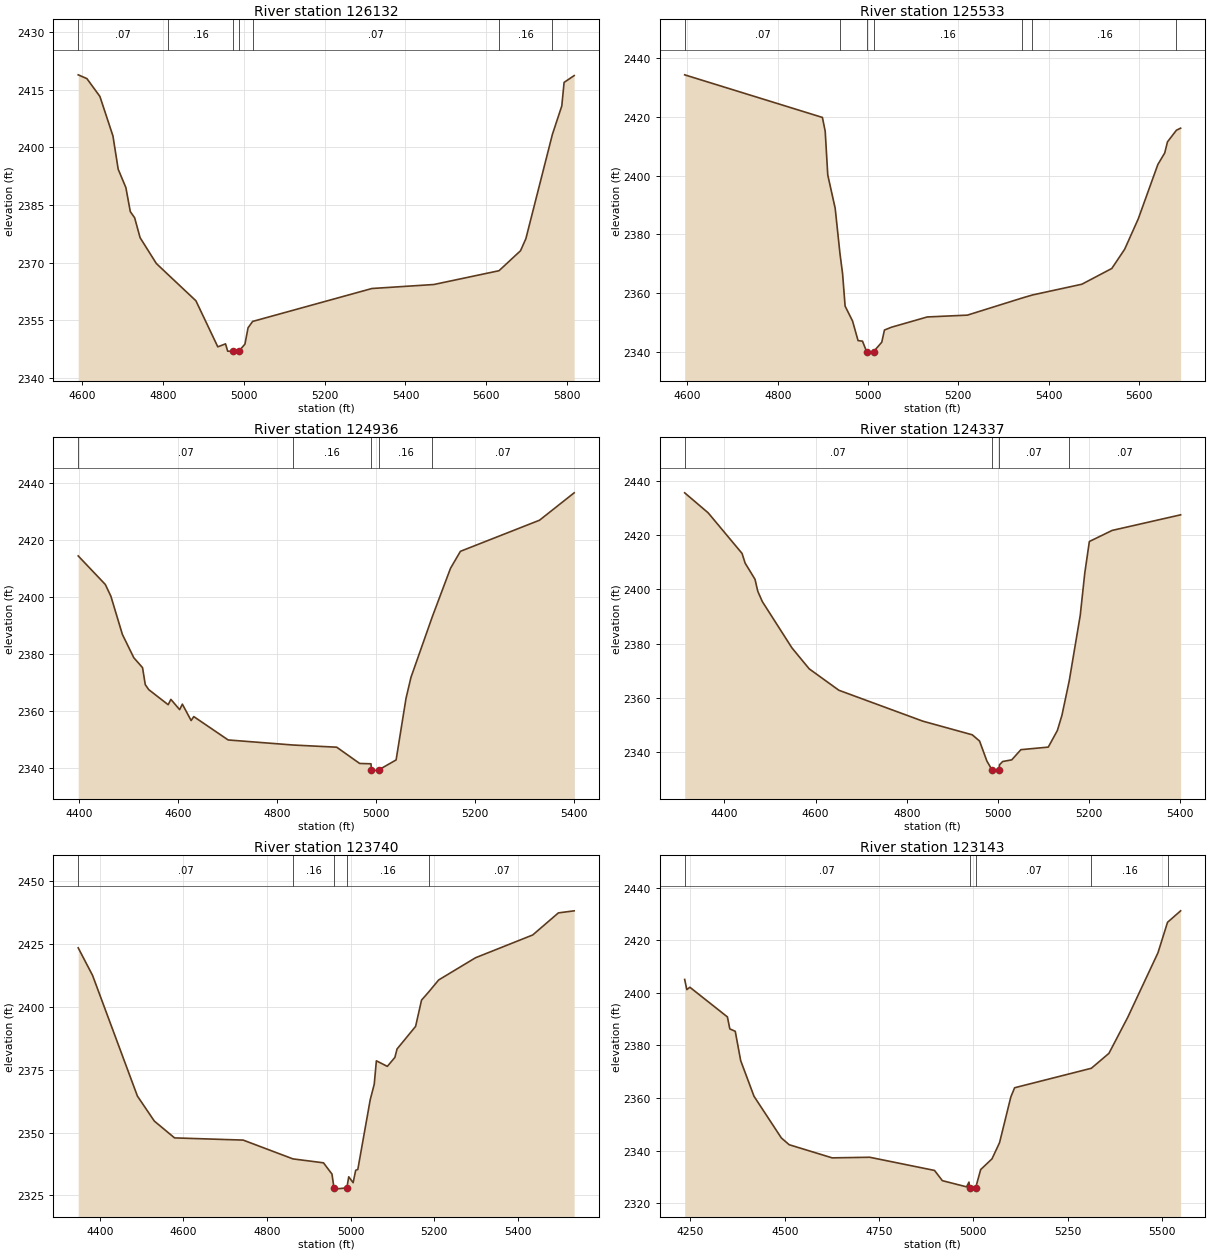
Type RM Length L Ch R = 1,126132,599,599,599
BEGIN DESCRIPTION:
Bitter Creek 136.0
END DESCRIPTION:
XS GIS Cut Line= 3
      1425454.99      6799788.03      1425604.88      6799406.20
      1426404.99      6799238.00
#Sta/Elev= 30
  4589.8 2418.84  4611.3 2417.86  4643.5 2413.22  4675.8 2402.94  4688.8 2394.28
  4707.8 2389.51  4718.8 2383.25  4729.5 2381.65  4743.0 2376.48  4783.2 2369.76
  4812.4 2366.86  4881.2 2360.06  4935.4 2348.08  4954.5 2348.85  4959.9 2346.94
  4972.3 2346.94  4972.6 2346.44  4987.6 2346.94  5002.6 2348.79  5010.3 2353.04
  5021.7 2354.69  5316.9 2363.25  5470.2 2364.29  5631.6 2367.88  5684.8 2373.07
  5698.1 2376.22  5763.7 2403.33  5787.0 2410.75  5792.7 2416.87  5817.6 2418.64
#Mann=7,-1,0
  4589.8    0.07       0  4812.4    0.16       0  4972.3    0.07       0
  4987.6    0.16       0  5021.7    0.07       0  5631.6    0.16       0
  5763.7    0.07       0
Bank Sta=4972.3,4987.6
Exp/Cntr=0.3,0.1

Type RM Length L Ch R = 1,125533,597,597,597
BEGIN DESCRIPTION:
Bitter Creek 135.0
END DESCRIPTION:
XS GIS Cut Line= 3
      1425555.00      6800038.00      1425914.52      6799849.15
      1426505.03      6799487.98
#Sta/Elev= 30
  4593.9 2434.33  4898.9 2419.83  4905.1 2415.15  4910.8 2400.25  4927.2 2388.92
  4937.8 2373.51  4943.6 2366.63  4949.2 2355.62  4965.6 2350.58  4977.9 2343.88
  4987.7 2343.69  4996.9 2340.12  4997.2 2339.62  5012.2 2340.12  5030.4 2343.34
  5036.3 2347.48  5051.7 2348.43  5131.1 2351.93  5220.0 2352.55  5341.7 2358.40
  5364.1 2359.41  5473.5 2363.07  5539.8 2368.43  5568.3 2374.98  5598.4 2385.32
  5641.8 2403.82  5657.0 2407.74  5663.1 2411.52  5682.9 2415.48  5692.2 2416.18
#Mann=7,-1,0
  4593.9    0.07       0  4937.8    0.16       0  4996.9    0.07       0
  5012.2    0.16       0  5341.7    0.07       0  5364.1    0.16       0
  5682.9    0.07       0
Bank Sta=4996.9,5012.2
Exp/Cntr=0.3,0.1

Type RM Length L Ch R = 1,124936,599,599,599
BEGIN DESCRIPTION:
Bitter Creek 134.0
END DESCRIPTION:
XS GIS Cut Line= 3
      1425905.02      6800187.99      1426453.78      6799941.44
      1426854.96      6799938.00
#Sta/Elev= 30
  4398.4 2414.37  4453.2 2404.35  4464.5 2400.21  4487.7 2386.83  4510.8 2378.64
  4528.5 2375.15  4534.0 2369.20  4540.9 2367.46  4580.3 2362.15  4585.8 2364.02
  4603.5 2360.42  4609.0 2362.35  4626.7 2356.60  4632.1 2357.98  4701.6 2349.78
  4833.2 2348.00  4921.1 2347.24  4967.4 2341.54  4990.4 2341.41  4991.4 2339.34
  4991.6 2338.84  5006.7 2339.34  5041.2 2342.77  5061.2 2364.36  5071.2 2371.73
  5114.3 2392.99  5151.2 2410.03  5171.2 2415.98  5331.2 2426.90  5401.2 2436.51
#Mann=5,-1,0
  4398.4    0.07       0  4833.2    0.16       0  4991.4    0.07       0
  5006.7    0.16       0  5114.3    0.07       0
Bank Sta=4991.4,5006.7
Exp/Cntr=0.3,0.1

Type RM Length L Ch R = 1,124337,597,597,597
BEGIN DESCRIPTION:
Bitter Creek 133.0
END DESCRIPTION:
XS GIS Cut Line= 3
      1425955.03      6800837.98      1426554.86      6800503.06
      1426954.98      6800488.00
#Sta/Elev= 30
  4313.0 2435.61  4364.4 2428.25  4438.9 2413.23  4445.5 2409.69  4467.2 2403.71
  4473.3 2399.29  4483.2 2395.50  4548.3 2378.37  4586.0 2370.67  4651.1 2362.76
  4835.1 2351.36  4943.6 2346.32  4959.6 2344.02  4975.6 2336.65  4986.7 2333.42
  4986.9 2332.92  5002.1 2333.42  5003.3 2335.24  5010.1 2336.46  5030.2 2337.09
  5050.2 2340.84  5110.2 2341.78  5130.2 2347.93  5140.2 2353.54  5156.2 2366.26
  5180.3 2390.39  5190.3 2406.06  5200.3 2417.65  5250.3 2421.74  5400.4 2427.49
#Mann=4,-1,0
  4313.0    0.07       0  4986.7    0.07       0  5002.1    0.07       0
  5156.2    0.07       0
Bank Sta=4986.7,5002.1
Exp/Cntr=0.3,0.1

Type RM Length L Ch R = 1,123740,597,597,597
BEGIN DESCRIPTION:
Bitter Creek 132.0
END DESCRIPTION:
XS GIS Cut Line= 3
      1426154.98      6801088.00      1426799.32      6800990.31
      1427321.89      6801102.10
#Sta/Elev= 30
  4348.3 2423.36  4382.7 2412.38  4489.9 2364.47  4530.4 2354.53  4578.8 2347.86
  4742.8 2346.99  4861.9 2339.52  4934.9 2337.96  4955.2 2333.49  4960.0 2328.01
  4960.5 2327.51  4990.8 2328.01  4995.3 2332.41  5005.8 2330.07  5011.9 2335.00
  5017.0 2335.32  5046.7 2363.04  5056.3 2369.20  5061.4 2378.48  5087.6 2376.27
  5105.7 2379.84  5110.8 2383.17  5155.2 2392.15  5169.4 2402.59  5186.3 2405.78
  5210.3 2410.59  5298.5 2419.42  5435.3 2428.47  5496.7 2437.24  5534.4 2438.06
#Mann=5,-1,0
  4348.3    0.07       0  4861.9    0.16       0  4960.0    0.07       0
  4990.8    0.16       0  5186.3    0.07       0
Bank Sta=4960,4990.8
Exp/Cntr=0.3,0.1

Type RM Length L Ch R = 1,123143,594,594,594
BEGIN DESCRIPTION:
Bitter Creek 131.0
END DESCRIPTION:
XS GIS Cut Line= 3
      1426101.78      6802023.59      1426705.44      6801553.18
      1427255.04      6801538.00
#Sta/Elev= 30
  4234.7 2405.06  4240.4 2401.20  4248.5 2402.10  4348.0 2390.82  4354.4 2386.26
  4368.8 2385.35  4383.3 2374.16  4418.6 2360.63  4491.0 2344.80  4511.8 2342.22
  4625.8 2337.22  4725.3 2337.45  4897.2 2332.44  4918.0 2328.55  4982.2 2326.20
  4988.6 2328.00  4990.3 2325.83  4990.5 2325.33  5006.3 2325.83  5019.6 2332.77
  5049.6 2336.84  5069.6 2342.98  5099.6 2360.40  5109.6 2363.88  5313.1 2371.29
  5359.7 2376.96  5409.7 2390.70  5489.7 2415.20  5515.1 2426.80  5549.8 2431.16
#Mann=5,-1,0
  4234.7    0.07       0  4990.3    0.07       0  5006.3    0.07       0
  5313.1    0.16       0  5515.1    0.07       0
Bank Sta=4990.3,5006.3
Exp/Cntr=0.3,0.1

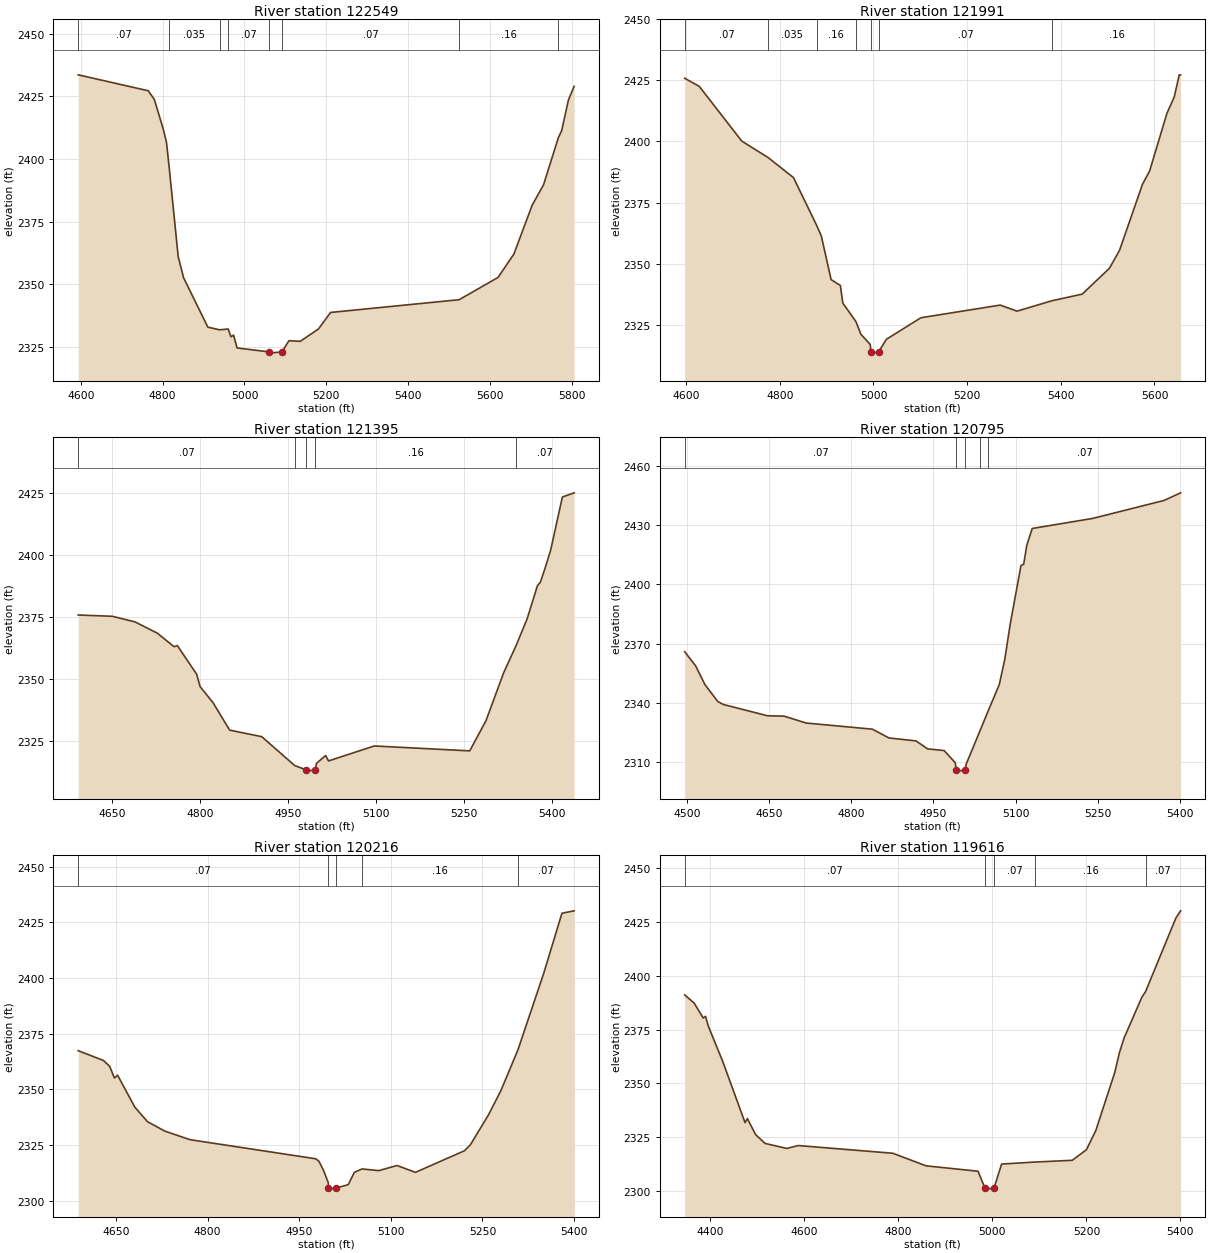
Type RM Length L Ch R = 1,122549,558,558,558
BEGIN DESCRIPTION:
Bitter Creek 130.0
END DESCRIPTION:
XS GIS Cut Line= 3
      1426255.02      6802337.99      1426587.54      6802104.69
      1427304.97      6801738.02
#Sta/Elev= 30
  4593.8 2433.61  4765.0 2427.24  4779.9 2423.73  4801.4 2412.05  4809.5 2406.64
  4815.8 2397.11  4838.1 2361.07  4851.3 2352.53  4910.6 2332.80  4939.2 2331.74
  4960.3 2332.06  4967.2 2328.95  4973.4 2329.60  4982.1 2324.49  5059.8 2322.92
  5060.3 2322.42  5091.8 2322.92  5108.7 2327.38  5136.5 2327.14  5181.0 2332.09
  5210.5 2338.67  5524.8 2343.77  5619.7 2352.66  5658.5 2362.02  5703.0 2381.50
  5730.8 2389.63  5767.3 2408.58  5775.2 2411.31  5791.8 2423.61  5805.7 2429.01
#Mann=8,-1,0
  4593.8    0.07       0  4815.8   0.035       0  4939.2    0.16       0
  4960.3    0.07       0  5059.8    0.07       0  5091.8    0.07       0
  5524.8    0.16       0  5767.3    0.07       0
Bank Sta=5059.8,5091.8
Exp/Cntr=0.3,0.1

Type RM Length L Ch R = 1,121991,596,596,596
BEGIN DESCRIPTION:
Bitter Creek 129.0
END DESCRIPTION:
XS GIS Cut Line= 3
      1426555.02      6802537.99      1426941.84      6802424.24
      1427505.00      6802088.00
#Sta/Elev= 30
  4596.8 2425.85  4628.0 2422.52  4718.7 2400.14  4774.8 2393.42  4829.2 2385.19
  4878.8 2365.58  4888.6 2361.31  4909.5 2343.45  4929.3 2341.05  4934.5 2333.84
  4962.6 2326.25  4973.1 2321.09  4992.9 2316.95  4995.0 2313.86  4995.3 2313.36
  5011.0 2313.86  5027.4 2319.00  5101.3 2327.84  5270.6 2333.02  5306.5 2330.54
  5381.8 2334.83  5445.8 2337.51  5504.1 2348.13  5525.5 2355.45  5574.4 2382.43
  5589.7 2387.91  5626.7 2411.49  5642.3 2418.20  5653.0 2427.25  5655.9 2427.25
#Mann=7,-1,0
  4596.8    0.07       0  4774.8   0.035       0  4878.8    0.16       0
  4962.6    0.07       0  4995.0    0.07       0  5011.0    0.07       0
  5381.8    0.16       0
Bank Sta=4995,5011
Exp/Cntr=0.3,0.1

Type RM Length L Ch R = 1,121395,600,600,600
BEGIN DESCRIPTION:
Bitter Creek 128.0
END DESCRIPTION:
XS GIS Cut Line= 3
      1427105.02      6802837.99      1427468.20      6802651.65
      1427904.99      6802688.00
#Sta/Elev= 30
  4591.8 2375.94  4650.1 2375.42  4688.8 2373.15  4726.7 2368.63  4755.4 2363.14
  4761.0 2363.59  4794.1 2351.99  4799.8 2347.04  4822.0 2340.52  4850.3 2329.46
  4905.1 2326.81  4961.2 2315.17  4980.7 2313.40  4980.9 2312.90  4996.7 2313.40
  4998.5 2316.05  5014.1 2319.20  5019.1 2317.02  5097.1 2323.06  5260.1 2321.08
  5287.8 2333.26  5317.9 2352.57  5339.4 2363.70  5358.0 2374.36  5375.6 2387.75
  5380.6 2389.17  5388.1 2394.43  5398.2 2402.12  5418.2 2423.58  5438.3 2425.27
#Mann=5,-1,0
  4591.8    0.07       0  4961.2    0.16       0  4980.7    0.07       0
  4996.7    0.16       0  5339.4    0.07       0
Bank Sta=4980.7,4996.7
Exp/Cntr=0.3,0.1

Type RM Length L Ch R = 1,120795,579,579,579
BEGIN DESCRIPTION:
Bitter Creek 127.0
END DESCRIPTION:
XS GIS Cut Line= 3
      1427205.02      6803038.00      1427705.11      6803103.04
      1428104.98      6803138.00
#Sta/Elev= 30
  4495.7 2365.91  4515.8 2358.69  4532.7 2349.25  4556.2 2340.66  4566.3 2339.17
  4646.9 2333.44  4677.2 2333.26  4717.5 2329.77  4838.5 2326.65  4868.8 2322.20
  4918.2 2320.71  4939.4 2316.67  4969.6 2315.82  4989.8 2309.69  4991.9 2305.90
  4992.1 2305.40  5008.0 2305.90  5009.9 2309.01  5035.1 2325.88  5049.8 2335.80
  5070.2 2349.18  5080.2 2361.92  5090.2 2379.84  5109.8 2409.49  5114.8 2410.20
  5120.4 2419.69  5130.4 2428.32  5240.8 2433.41  5371.3 2442.53  5401.4 2446.38
#Mann=5,-1,0
  4495.7    0.07       0  4991.9    0.07       0  5008.0    0.07       0
  5035.1    0.16       0  5049.8    0.07       0
Bank Sta=4991.9,5008
Exp/Cntr=0.3,0.1

Type RM Length L Ch R = 1,120216,600,600,600
BEGIN DESCRIPTION:
Bitter Creek 126.0
END DESCRIPTION:
XS GIS Cut Line= 3
      1427054.96      6803487.99      1427454.67      6803587.86
      1427854.97      6803588.00
#Sta/Elev= 30
  4588.0 2367.33  4629.3 2362.95  4639.6 2360.28  4647.3 2355.07  4652.5 2356.33
  4680.8 2341.96  4701.4 2335.48  4729.8 2331.23  4771.1 2327.38  4977.3 2318.78
  4982.4 2317.62  4990.0 2313.48  4997.6 2308.06  4997.7 2305.67  4997.9 2305.17
  5010.6 2305.67  5030.3 2307.17  5040.3 2312.71  5052.9 2314.24  5080.3 2313.48
  5110.3 2315.78  5140.3 2312.70  5220.3 2322.36  5230.3 2325.05  5260.3 2338.68
  5280.3 2349.40  5308.3 2367.75  5350.3 2401.95  5380.3 2429.06  5400.3 2430.14
#Mann=5,-1,0
  4588.0    0.07       0  4997.7    0.07       0  5010.6    0.07       0
  5052.9    0.16       0  5308.3    0.07       0
Bank Sta=4997.7,5010.6
Exp/Cntr=0.3,0.1

Type RM Length L Ch R = 1,119616,577,577,577
BEGIN DESCRIPTION:
Bitter Creek 125.0
END DESCRIPTION:
XS GIS Cut Line= 3
      1426805.02      6804188.00      1427455.41      6804113.00
      1427855.03      6804088.00
#Sta/Elev= 30
  4345.3 2391.12  4365.4 2387.35  4384.7 2380.40  4389.7 2381.18  4395.6 2376.62
  4425.8 2360.49  4473.7 2331.84  4478.7 2333.70  4496.3 2326.25  4516.4 2322.18
  4562.6 2319.84  4586.9 2321.20  4788.2 2317.61  4858.7 2311.78  4969.4 2309.26
  4984.0 2301.46  4984.3 2300.96  5003.4 2301.46  5019.6 2312.60  5091.2 2313.54
  5169.9 2314.34  5200.0 2319.26  5220.0 2328.18  5260.1 2354.96  5270.1 2364.20
  5280.1 2371.09  5317.7 2389.93  5326.0 2392.74  5390.3 2426.79  5400.4 2430.15
#Mann=5,-1,0
  4345.3    0.07       0  4984.0    0.07       0  5003.4    0.07       0
  5091.2    0.16       0  5326.0    0.07       0
Bank Sta=4984,5003.4
Exp/Cntr=0.3,0.1