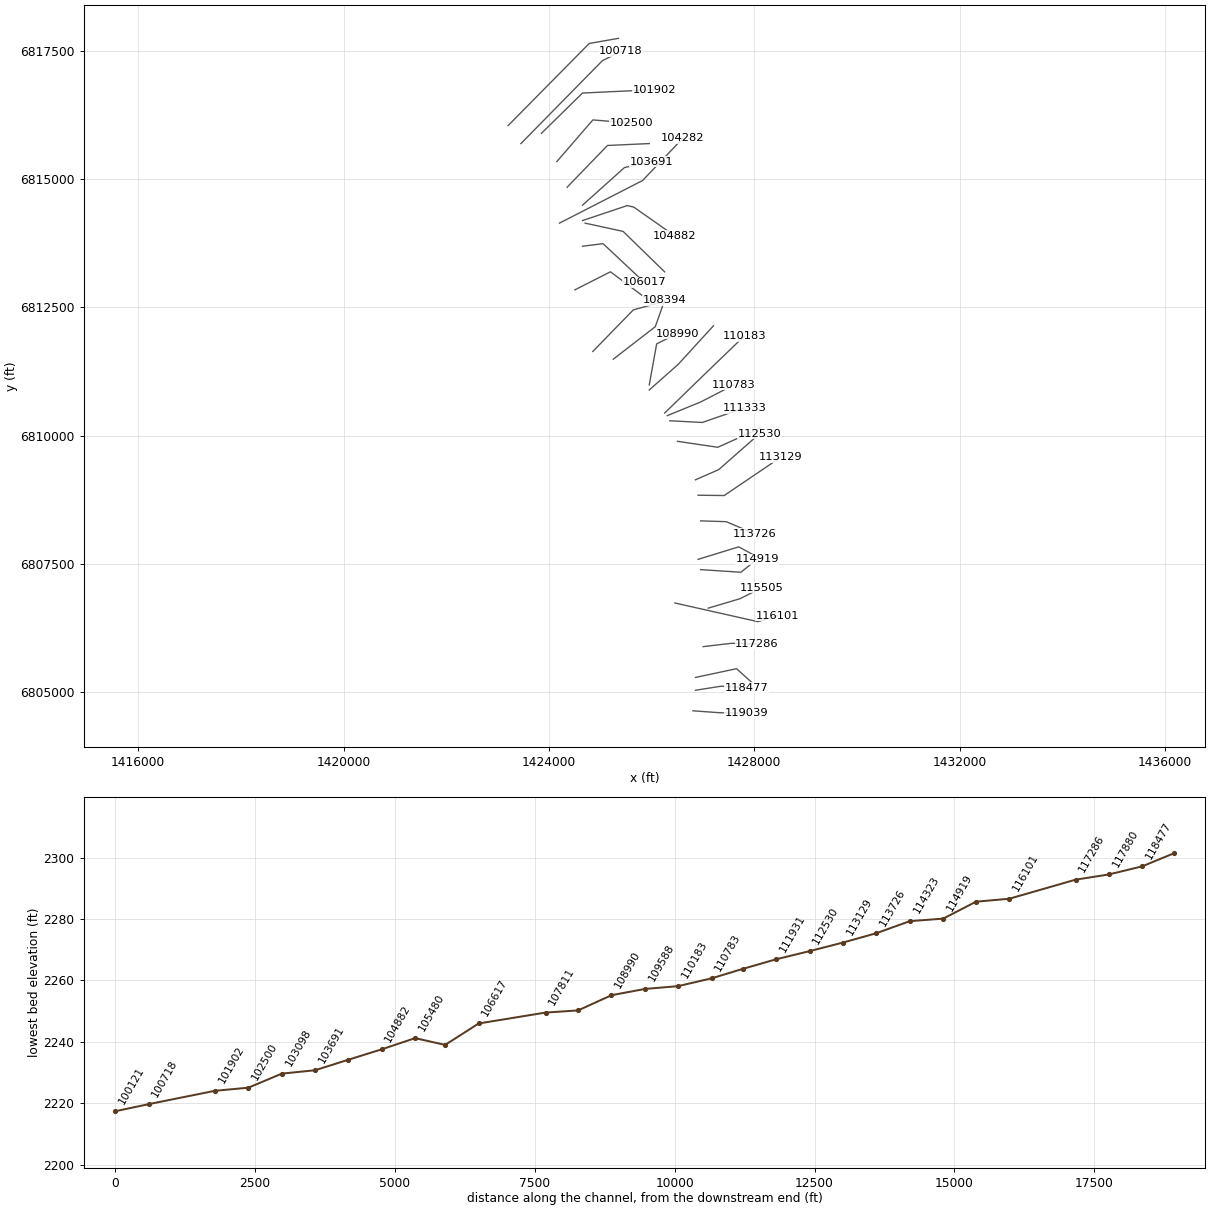
HEC-RAS study Bitter Creek.prj: Bitter Creek Base Level Engineering

--- Bitter Creek.g01 (geometry) --- (continued)

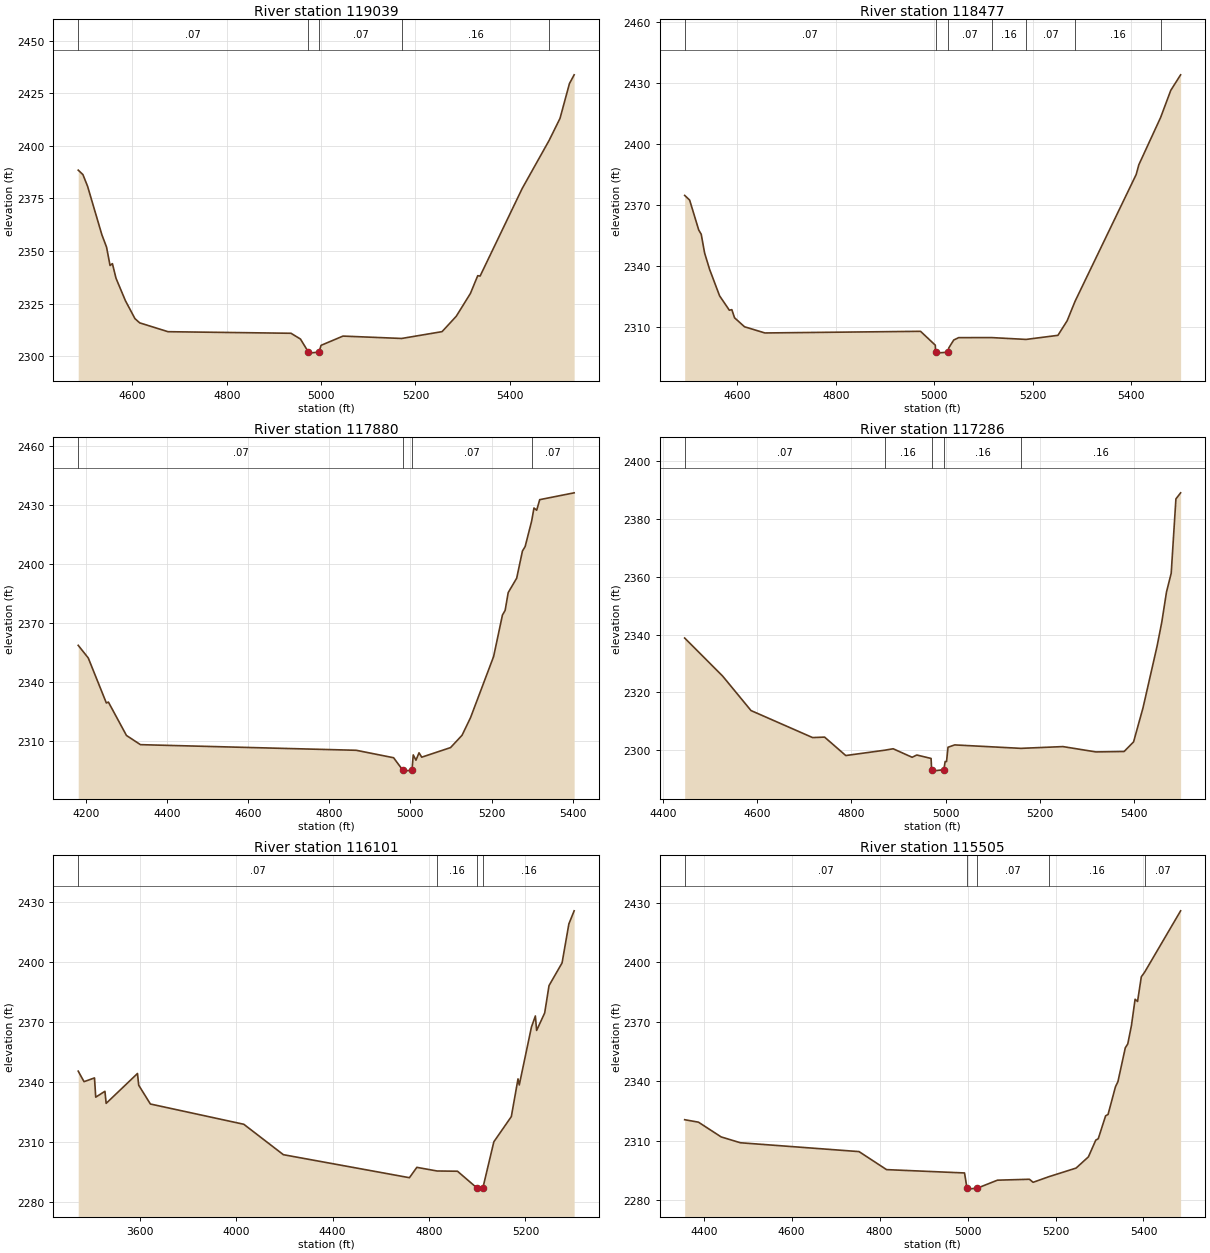
Type RM Length L Ch R = 1,119039,562,562,562
BEGIN DESCRIPTION:
Bitter Creek 124.0
END DESCRIPTION:
XS GIS Cut Line= 3
      1426805.04      6804638.00      1427318.52      6804601.16
      1427854.96      6804588.00
#Sta/Elev= 30
  4485.2 2388.50  4495.2 2386.37  4505.2 2380.73  4535.3 2357.78  4545.3 2351.84
  4552.7 2343.11  4557.7 2343.99  4565.4 2337.00  4585.4 2326.30  4605.5 2317.82
  4615.5 2315.81  4675.6 2311.60  4936.3 2310.85  4956.4 2308.10  4973.2 2301.90
  4973.5 2301.40  4995.8 2301.90  5000.0 2305.10  5046.5 2309.51  5170.9 2308.38
  5256.6 2311.63  5286.6 2318.93  5316.6 2329.77  5332.2 2338.26  5337.2 2338.08
  5426.6 2379.83  5483.6 2402.67  5506.6 2413.12  5526.6 2429.68  5536.6 2433.86
#Mann=5,-1,0
  4485.2    0.07       0  4973.2    0.07       0  4995.8    0.07       0
  5170.9    0.16       0  5483.6    0.07       0
Bank Sta=4973.2,4995.8
Exp/Cntr=0.3,0.1

Type RM Length L Ch R = 1,118477,597,597,597
BEGIN DESCRIPTION:
Bitter Creek 123.0
END DESCRIPTION:
XS GIS Cut Line= 3
      1426855.00      6805038.00      1427355.40      6805117.68
      1427855.01      6805088.00
#Sta/Elev= 30
  4493.3 2374.85  4503.4 2372.54  4521.9 2357.78  4526.9 2355.74  4533.8 2346.47
  4543.9 2338.45  4564.2 2325.41  4584.0 2318.33  4589.1 2318.59  4594.6 2314.59
  4614.8 2310.17  4656.3 2307.12  4972.3 2307.93  5002.3 2301.10  5002.8 2297.69
  5003.2 2297.19  5028.6 2297.69  5029.7 2299.76  5039.7 2303.64  5049.7 2304.82
  5116.8 2304.84  5186.7 2303.94  5251.3 2305.95  5270.1 2313.14  5286.1 2322.70
  5410.3 2385.17  5415.7 2389.98  5459.9 2413.23  5480.5 2426.59  5500.5 2434.23
#Mann=7,-1,0
  4493.3    0.07       0  5002.8    0.07       0  5028.6    0.07       0
  5116.8    0.16       0  5186.7    0.07       0  5286.1    0.16       0
  5459.9    0.07       0
Bank Sta=5002.8,5028.6
Exp/Cntr=0.3,0.1

Type RM Length L Ch R = 1,117880,594,594,594
BEGIN DESCRIPTION:
Bitter Creek 122.0
END DESCRIPTION:
XS GIS Cut Line= 3
      1426854.97      6805287.99      1427655.46      6805458.25
      1427954.98      6805188.02
#Sta/Elev= 30
  4181.6 2358.47  4206.4 2352.03  4250.9 2329.18  4256.0 2329.62  4300.5 2312.66
  4335.0 2307.99  4866.6 2305.13  4958.6 2301.34  4981.2 2295.04  4981.6 2294.54
  5003.9 2295.04  5007.0 2302.78  5013.7 2300.10  5021.2 2303.85  5027.9 2301.63
  5098.9 2306.50  5127.3 2312.79  5148.2 2321.75  5205.0 2352.79  5226.7 2373.84
  5233.4 2376.26  5240.9 2385.26  5261.8 2392.59  5276.0 2406.39  5282.7 2408.69
  5298.7 2421.61  5304.4 2428.26  5311.1 2427.12  5318.6 2432.50  5403.4 2435.97
#Mann=4,-1,0
  4181.6    0.07       0  4981.2    0.07       0  5003.9    0.07       0
  5298.7    0.07       0
Bank Sta=4981.2,5003.9
Exp/Cntr=0.3,0.1

Type RM Length L Ch R = 1,117286,1185,1185,1185
BEGIN DESCRIPTION:
Bitter Creek 121.0
END DESCRIPTION:
XS GIS Cut Line= 3
      1427004.98      6805888.00      1427555.53      6805953.19
      1428055.00      6805938.00
#Sta/Elev= 30
  4445.6 2338.79  4526.2 2325.67  4586.6 2313.75  4717.5 2304.42  4743.0 2304.58
  4788.0 2298.22  4870.7 2300.06  4888.7 2300.56  4929.0 2297.62  4939.0 2298.40
  4969.3 2297.22  4970.5 2293.34  4971.0 2292.84  4996.4 2293.34  4999.2 2296.15
  5002.2 2296.15  5005.3 2301.08  5019.5 2301.89  5160.3 2300.70  5249.6 2301.31
  5319.6 2299.47  5379.6 2299.62  5399.7 2302.93  5419.7 2314.65  5449.7 2336.01
  5459.7 2344.30  5469.7 2354.69  5479.7 2361.15  5489.7 2386.80  5499.7 2388.91
#Mann=5,-1,0
  4445.6    0.07       0  4870.7    0.16       0  4970.5    0.07       0
  4996.4    0.16       0  5160.3    0.16       0
Bank Sta=4970.5,4996.4
Exp/Cntr=0.3,0.1

Type RM Length L Ch R = 1,116101,596,596,596
BEGIN DESCRIPTION:
Bitter Creek 120.0
END DESCRIPTION:
XS GIS Cut Line= 3
      1426454.96      6806738.01      1428069.13      6806374.93
      1428455.00      6806488.00
#Sta/Elev= 30
  3345.5 2345.56  3369.7 2340.30  3413.0 2342.18  3418.2 2332.57  3456.3 2335.50
  3461.4 2329.46  3591.3 2344.39  3596.4 2338.53  3644.8 2329.15  4032.3 2319.02
  4196.3 2303.83  4719.0 2292.34  4749.8 2297.51  4833.6 2295.69  4918.3 2295.57
  4999.8 2287.13  5000.2 2286.63  5023.4 2287.13  5069.1 2310.27  5141.6 2322.86
  5169.3 2341.69  5174.5 2338.66  5224.9 2367.53  5241.3 2373.12  5246.5 2365.90
  5279.9 2374.63  5297.9 2388.29  5352.0 2399.62  5380.2 2419.10  5402.1 2425.64
#Mann=4,-1,0
  3345.5    0.07       0  4833.6    0.16       0  4999.8    0.07       0
  5023.4    0.16       0
Bank Sta=4999.8,5023.4
Exp/Cntr=0.3,0.1

Type RM Length L Ch R = 1,115505,586,586,586
BEGIN DESCRIPTION:
Bitter Creek 119.0
END DESCRIPTION:
XS GIS Cut Line= 3
      1427105.01      6806638.00      1427721.59      6806821.48
      1428155.01      6807038.01
#Sta/Elev= 30
  4356.7 2320.64  4388.0 2319.41  4439.6 2311.98  4483.3 2309.03  4753.2 2304.57
  4815.8 2295.49  4993.1 2293.81  4998.7 2286.16  4999.2 2285.66  5022.3 2286.16
  5067.9 2290.17  5140.6 2290.63  5149.1 2289.10  5184.3 2291.88  5246.8 2296.27
  5274.8 2301.92  5291.6 2310.36  5297.2 2311.06  5313.9 2322.59  5319.5 2323.30
  5336.3 2337.22  5341.9 2339.79  5358.7 2356.87  5364.3 2358.83  5372.7 2368.16
  5381.0 2381.35  5386.6 2380.24  5395.1 2392.67  5402.4 2394.89  5484.5 2425.91
#Mann=5,-1,0
  4356.7    0.07       0  4998.7    0.07       0  5022.3    0.07       0
  5184.3    0.16       0  5402.4    0.07       0
Bank Sta=4998.7,5022.3
Exp/Cntr=0.3,0.1

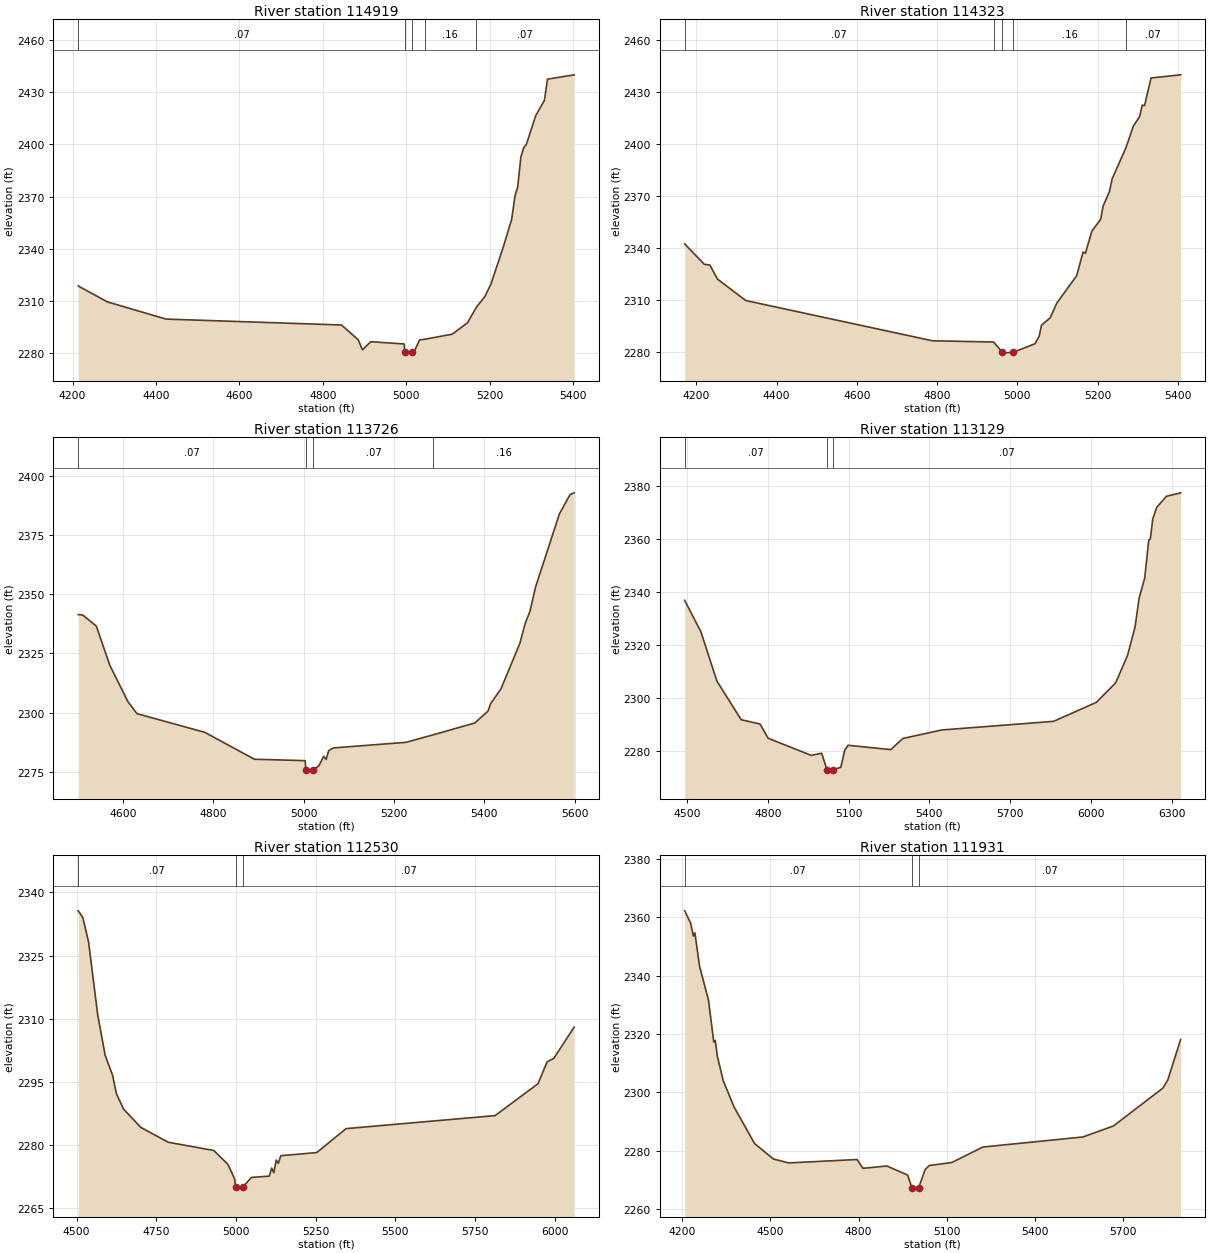
Type RM Length L Ch R = 1,114919,596,596,596
BEGIN DESCRIPTION:
Bitter Creek 118.0
END DESCRIPTION:
XS GIS Cut Line= 3
      1426954.96      6807388.00      1427739.72      6807337.16
      1428055.01      6807588.00
#Sta/Elev= 30
  4213.6 2318.69  4283.8 2309.54  4424.1 2299.69  4845.0 2296.29  4885.0 2287.83
  4895.1 2282.03  4915.1 2286.69  4995.1 2285.41  4997.2 2280.64  4997.6 2280.14
  5014.1 2280.64  5019.3 2281.10  5032.3 2287.72  5044.2 2288.10  5110.6 2291.03
  5147.3 2297.60  5167.9 2306.27  5189.1 2312.79  5203.5 2319.91  5232.3 2340.59
  5253.1 2356.98  5261.2 2370.58  5267.5 2375.46  5275.1 2392.73  5282.0 2398.10
  5288.4 2400.03  5310.8 2416.53  5331.6 2425.29  5339.0 2437.45  5402.9 2439.94
#Mann=5,-1,0
  4213.6    0.07       0  4997.2    0.07       0  5014.1    0.07       0
  5044.2    0.16       0  5167.9    0.07       0
Bank Sta=4997.2,5014.1
Exp/Cntr=0.3,0.1

Type RM Length L Ch R = 1,114323,597,597,597
BEGIN DESCRIPTION:
Bitter Creek 117.0
END DESCRIPTION:
XS GIS Cut Line= 3
      1426905.00      6807588.00      1427697.22      6807831.84
      1428054.99      6807638.01
#Sta/Elev= 30
  4171.1 2342.37  4220.1 2330.55  4233.9 2330.20  4252.8 2322.07  4323.4 2309.68
  4788.4 2286.46  4940.7 2285.75  4963.0 2279.83  4963.6 2279.33  4990.1 2279.83
  5044.1 2284.76  5054.3 2289.00  5060.3 2295.45  5082.2 2299.80  5098.3 2308.17
  5147.8 2323.99  5163.9 2337.65  5169.6 2336.92  5185.8 2349.77  5207.7 2356.54
  5213.6 2364.04  5229.6 2372.60  5236.3 2379.92  5270.6 2397.83  5289.5 2410.56
  5304.6 2415.76  5311.3 2422.46  5317.0 2422.17  5333.2 2438.12  5406.9 2439.93
#Mann=5,-1,0
  4171.1    0.07       0  4940.7    0.16       0  4963.0    0.07       0
  4990.1    0.16       0  5270.6    0.07       0
Bank Sta=4963,4990.1
Exp/Cntr=0.3,0.1

Type RM Length L Ch R = 1,113726,597,597,597
BEGIN DESCRIPTION:
Bitter Creek 116.0
END DESCRIPTION:
XS GIS Cut Line= 3
      1426954.95      6808338.00      1427454.11      6808322.34
      1428005.03      6808087.99
#Sta/Elev= 30
  4500.6 2341.38  4510.7 2341.22  4540.7 2336.56  4570.7 2319.98  4610.7 2304.69
  4630.7 2299.63  4780.8 2291.76  4890.8 2280.41  5003.2 2279.81  5004.6 2275.90
  5004.9 2275.40  5021.5 2275.90  5033.6 2277.70  5044.2 2281.63  5049.6 2280.36
  5055.3 2284.08  5066.2 2285.19  5226.0 2287.53  5286.9 2290.72  5378.7 2295.70
  5407.8 2300.66  5413.9 2303.88  5436.9 2310.18  5478.7 2329.39  5490.0 2337.52
  5500.9 2342.82  5513.2 2352.98  5566.1 2383.88  5589.6 2391.99  5598.7 2392.73
#Mann=4,-1,0
  4500.6    0.07       0  5004.6    0.07       0  5021.5    0.07       0
  5286.9    0.16       0
Bank Sta=5004.6,5021.5
Exp/Cntr=0.3,0.1

Type RM Length L Ch R = 1,113129,599,599,599
BEGIN DESCRIPTION:
Bitter Creek 115.0
END DESCRIPTION:
XS GIS Cut Line= 3
      1426904.97      6808838.00      1427414.12      6808831.37
      1428518.45      6809579.18
#Sta/Elev= 30
  4490.8 2336.75  4550.8 2324.96  4610.8 2306.25  4700.9 2291.73  4770.9 2290.12
  4800.9 2284.75  4960.9 2278.30  5000.0 2279.09  5019.5 2272.85  5020.0 2272.35
  5042.5 2272.85  5070.9 2273.81  5085.6 2280.23  5097.9 2282.10  5256.7 2280.47
  5301.5 2284.66  5445.3 2287.86  5861.8 2291.13  6020.5 2298.28  6092.4 2305.66
  6136.3 2315.96  6164.3 2326.67  6179.3 2337.50  6200.3 2345.18  6215.2 2359.43
  6221.3 2359.95  6230.2 2367.48  6245.0 2371.84  6281.1 2376.00  6333.7 2377.30
#Mann=3,-1,0
  4490.8    0.07       0  5019.5    0.07       0  5042.5    0.07       0
Bank Sta=5019.5,5042.5
Exp/Cntr=0.3,0.1

Type RM Length L Ch R = 1,112530,599,599,599
BEGIN DESCRIPTION:
Bitter Creek 114.0
END DESCRIPTION:
XS GIS Cut Line= 3
      1426855.00      6809138.00      1427308.55      6809336.53
      1428104.99      6810037.99
#Sta/Elev= 30
  4504.9 2335.64  4519.3 2334.07  4537.3 2328.30  4566.1 2310.93  4589.5 2301.34
  4612.9 2296.56  4625.0 2292.15  4647.2 2288.57  4701.4 2284.21  4787.5 2280.68
  4930.6 2278.72  4974.3 2275.46  4995.6 2272.03  4998.6 2270.05  4999.1 2269.55
  5021.6 2270.05  5048.5 2272.33  5104.6 2272.64  5112.1 2274.56  5118.8 2273.45
  5126.3 2276.45  5133.0 2275.68  5140.6 2277.49  5253.5 2278.23  5345.5 2283.92
  5813.2 2287.01  5947.9 2294.59  5976.4 2299.77  5997.3 2300.59  6061.3 2308.01
#Mann=3,-1,0
  4504.9    0.07       0  4998.6    0.07       0  5021.6    0.07       0
Bank Sta=4998.6,5021.6
Exp/Cntr=0.3,0.1

Type RM Length L Ch R = 1,111931,598,598,598
BEGIN DESCRIPTION:
Bitter Creek 113.0
END DESCRIPTION:
XS GIS Cut Line= 3
      1426504.99      6809888.00      1427288.16      6809771.45
      1428104.99      6810138.00
#Sta/Elev= 30
  4208.2 2362.25  4228.4 2358.09  4237.8 2353.61  4242.9 2354.73  4258.8 2343.28
  4289.1 2331.70  4307.2 2317.28  4312.2 2317.87  4319.4 2312.39  4339.6 2303.97
  4376.5 2294.99  4445.9 2282.52  4510.2 2277.21  4562.1 2275.87  4794.6 2277.04
  4814.8 2274.02  4895.7 2274.82  4966.5 2271.72  4981.3 2267.39  4981.8 2266.89
  5004.3 2267.39  5026.1 2273.59  5040.4 2274.98  5117.1 2276.02  5222.4 2281.31
  5563.3 2284.77  5666.9 2288.54  5834.6 2301.48  5851.5 2304.23  5895.3 2318.16
#Mann=3,-1,0
  4208.2    0.07       0  4981.3    0.07       0  5004.3    0.07       0
Bank Sta=4981.3,5004.3
Exp/Cntr=0.3,0.1

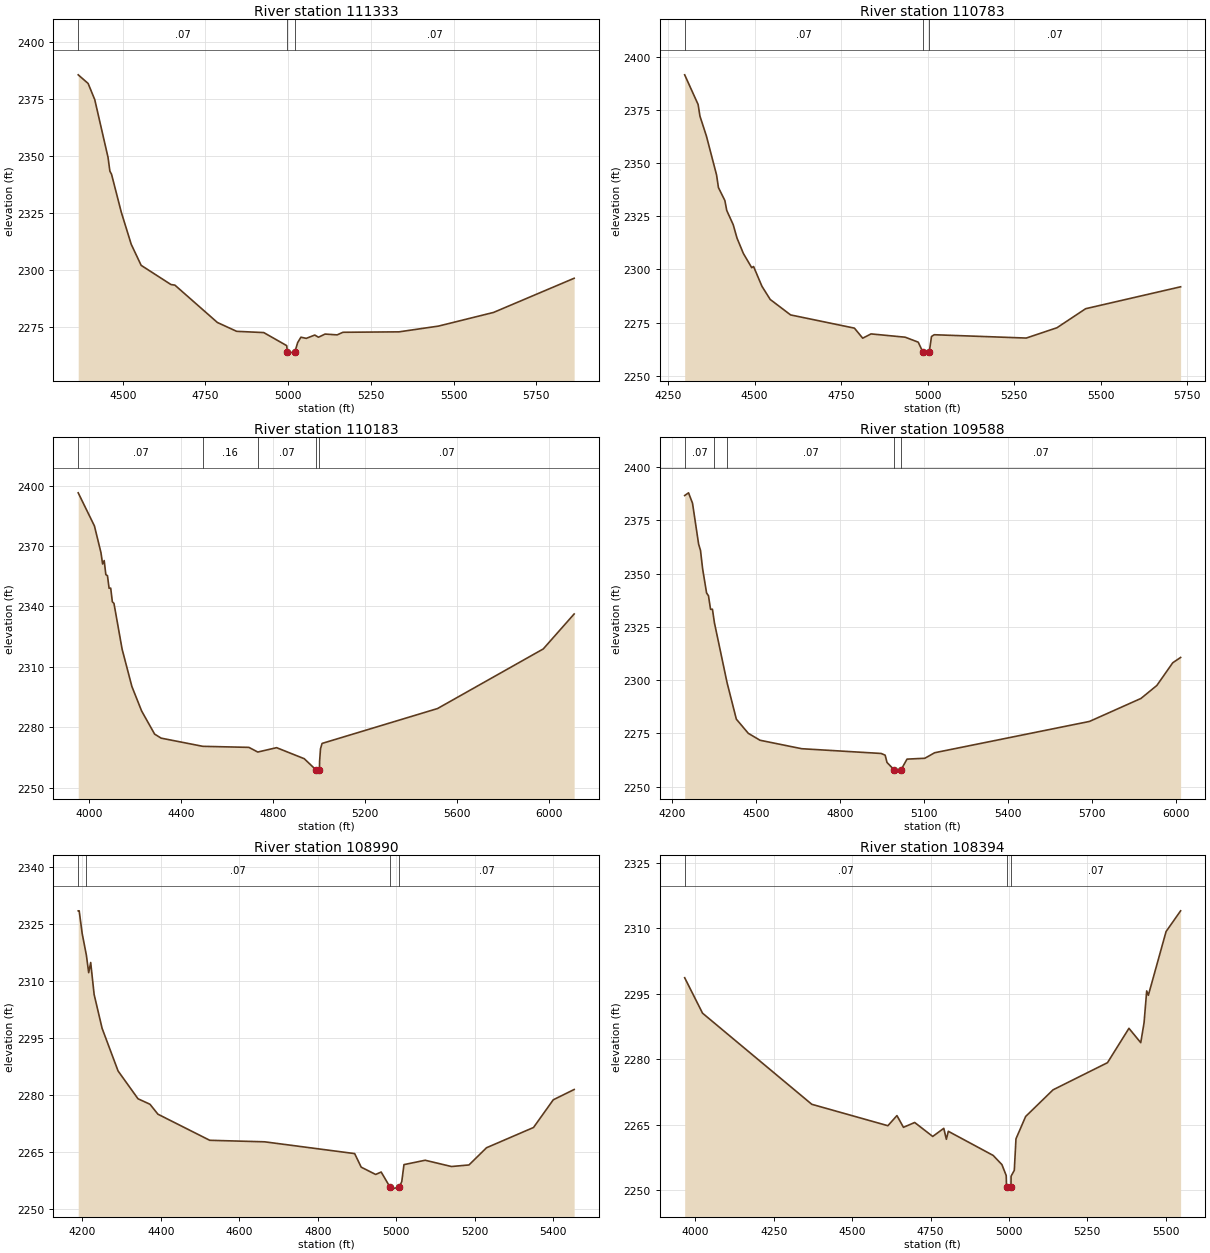
Type RM Length L Ch R = 1,111333,550,550,550
BEGIN DESCRIPTION:
Bitter Creek 112.0
END DESCRIPTION:
XS GIS Cut Line= 3
      1426355.03      6810288.00      1426988.58      6810255.08
      1427805.04      6810538.02
#Sta/Elev= 30
  4365.6 2385.53  4395.6 2381.75  4415.6 2374.67  4455.7 2349.41  4461.3 2343.38
  4466.3 2342.02  4495.7 2325.45  4525.8 2311.37  4555.8 2302.16  4645.9 2293.76
  4657.8 2293.50  4786.1 2277.16  4844.3 2273.29  4926.3 2272.74  4995.7 2267.02
  4997.2 2264.25  4997.7 2263.75  5020.2 2264.25  5028.7 2268.36  5038.5 2270.72
  5054.6 2270.21  5080.4 2271.66  5091.5 2270.71  5111.6 2272.09  5148.0 2271.74
  5165.5 2272.87  5334.9 2273.06  5454.2 2275.58  5620.6 2281.56  5864.1 2296.51
#Mann=3,-1,0
  4365.6    0.07       0  4997.2    0.07       0  5020.2    0.07       0
Bank Sta=4997.2,5020.2
Exp/Cntr=0.3,0.1

Type RM Length L Ch R = 1,110783,600,600,600
BEGIN DESCRIPTION:
Bitter Creek 111.0
END DESCRIPTION:
XS GIS Cut Line= 3
      1426305.00      6810388.00      1426954.75      6810653.22
      1427605.03      6810988.01
#Sta/Elev= 30
  4298.2 2391.45  4337.0 2377.53  4342.4 2372.01  4361.0 2362.70  4390.4 2344.37
  4395.8 2338.48  4414.4 2332.37  4419.8 2327.73  4438.5 2321.02  4449.4 2314.77
  4467.9 2307.51  4491.9 2300.87  4497.3 2301.39  4521.4 2292.14  4545.4 2285.92
  4604.3 2278.66  4788.7 2272.45  4812.7 2267.73  4836.8 2269.74  4935.5 2268.19
  4973.1 2265.86  4986.6 2261.21  4987.0 2260.71  5005.0 2261.21  5011.5 2268.53
  5019.3 2269.35  5285.3 2267.79  5374.0 2272.63  5457.0 2281.58  5731.4 2291.87
#Mann=3,-1,0
  4298.2    0.07       0  4986.6    0.07       0  5005.0    0.07       0
Bank Sta=4986.6,5005
Exp/Cntr=0.3,0.1

Type RM Length L Ch R = 1,110183,595,595,595
BEGIN DESCRIPTION:
Bitter Creek 110.0
END DESCRIPTION:
XS GIS Cut Line= 3
      1426255.03      6810438.03      1427005.39      6811167.64
      1427804.98      6811937.98
#Sta/Elev= 30
  3953.4 2396.39  4024.0 2379.92  4052.3 2366.71  4059.5 2361.04  4066.4 2362.74
  4073.6 2355.72  4080.6 2355.28  4087.7 2348.98  4094.7 2349.06  4101.9 2342.27
  4108.9 2341.46  4144.3 2318.76  4186.8 2300.21  4229.2 2288.03  4285.8 2276.53
  4314.1 2274.53  4495.2 2270.47  4695.8 2269.95  4734.4 2267.63  4816.2 2269.80
  4936.3 2264.33  4988.8 2258.65  4989.1 2258.15  5002.7 2258.65  5003.2 2262.91
  5007.1 2269.21  5014.0 2271.91  5516.2 2289.24  5975.9 2318.84  6110.3 2336.21
#Mann=5,-1,0
  3953.4    0.07       0  4495.2    0.16       0  4734.4    0.07       0
  4988.8    0.07       0  5002.7    0.07       0
Bank Sta=4988.8,5002.7
Exp/Cntr=0.3,0.1

Type RM Length L Ch R = 1,109588,598,598,598
BEGIN DESCRIPTION:
Bitter Creek 109.0
END DESCRIPTION:
XS GIS Cut Line= 3
      1425954.99      6810888.00      1426520.23      6811388.53
      1427205.00      6812138.01
#Sta/Elev= 30
  4245.0 2386.72  4258.8 2387.99  4273.0 2383.10  4294.8 2363.86  4301.5 2360.93
  4309.0 2352.36  4323.2 2340.93  4329.9 2339.64  4337.4 2333.25  4344.1 2333.30
  4351.3 2326.85  4396.5 2298.69  4429.4 2281.65  4472.1 2274.99  4513.9 2271.74
  4662.8 2267.76  4946.3 2265.53  4960.6 2264.72  4967.2 2261.30  4993.5 2257.73
  4994.0 2257.23  5016.8 2257.73  5038.6 2262.87  5102.2 2263.27  5137.3 2265.87
  5689.9 2280.58  5873.7 2291.38  5930.4 2297.48  5987.1 2308.15  6015.2 2310.64
#Mann=5,-1,0
  4245.0    0.07       0  4351.3    0.16       0  4396.5    0.07       0
  4993.5    0.07       0  5016.8    0.07       0
Bank Sta=4993.5,5016.8
Exp/Cntr=0.3,0.1

Type RM Length L Ch R = 1,108990,596,596,596
BEGIN DESCRIPTION:
Bitter Creek 108.0
END DESCRIPTION:
XS GIS Cut Line= 3
      1425955.01      6810988.05      1426099.14      6811785.93
      1426505.02      6811988.01
#Sta/Elev= 30
  4189.2 2328.43  4191.7 2328.43  4199.3 2322.47  4210.1 2316.71  4215.9 2312.15
  4221.0 2314.83  4229.8 2306.40  4250.1 2297.51  4290.8 2286.29  4341.6 2278.97
  4372.1 2277.53  4392.4 2274.91  4524.5 2268.04  4664.5 2267.64  4893.9 2264.54
  4910.6 2260.97  4947.4 2259.05  4961.5 2259.69  4984.2 2255.69  4984.7 2255.19
  5007.7 2255.69  5014.0 2257.18  5019.6 2261.64  5073.6 2262.79  5140.6 2261.14
  5185.3 2261.55  5230.0 2266.08  5349.8 2271.41  5400.2 2278.70  5453.4 2281.41
#Mann=4,-1,0
  4189.2    0.16       0  4210.1    0.07       0  4984.2    0.07       0
  5007.7    0.07       0
Bank Sta=4984.2,5007.7
Exp/Cntr=0.3,0.1

Type RM Length L Ch R = 1,108394,583,583,583
BEGIN DESCRIPTION:
Bitter Creek 107.0
END DESCRIPTION:
XS GIS Cut Line= 3
      1425255.04      6811488.03      1426072.63      6812121.53
      1426254.99      6812637.98
#Sta/Elev= 30
  3965.7 2298.71  4022.7 2290.58  4371.2 2269.69  4613.9 2264.78  4642.8 2267.10
  4663.6 2264.41  4699.4 2265.52  4756.9 2262.32  4792.2 2264.18  4800.4 2261.67
  4806.7 2263.50  4949.7 2257.97  4977.7 2255.86  4991.4 2253.35  4992.4 2250.74
  4992.7 2250.24  5006.6 2250.74  5006.9 2253.20  5017.2 2254.56  5022.5 2261.77
  5053.4 2266.90  5140.8 2273.01  5314.4 2279.23  5382.9 2287.11  5420.5 2283.82
  5431.1 2288.40  5439.5 2295.69  5444.8 2294.69  5501.3 2309.30  5547.7 2314.05
#Mann=3,-1,0
  3965.7    0.07       0  4992.4    0.07       0  5006.6    0.07       0
Bank Sta=4992.4,5006.6
Exp/Cntr=0.3,0.1

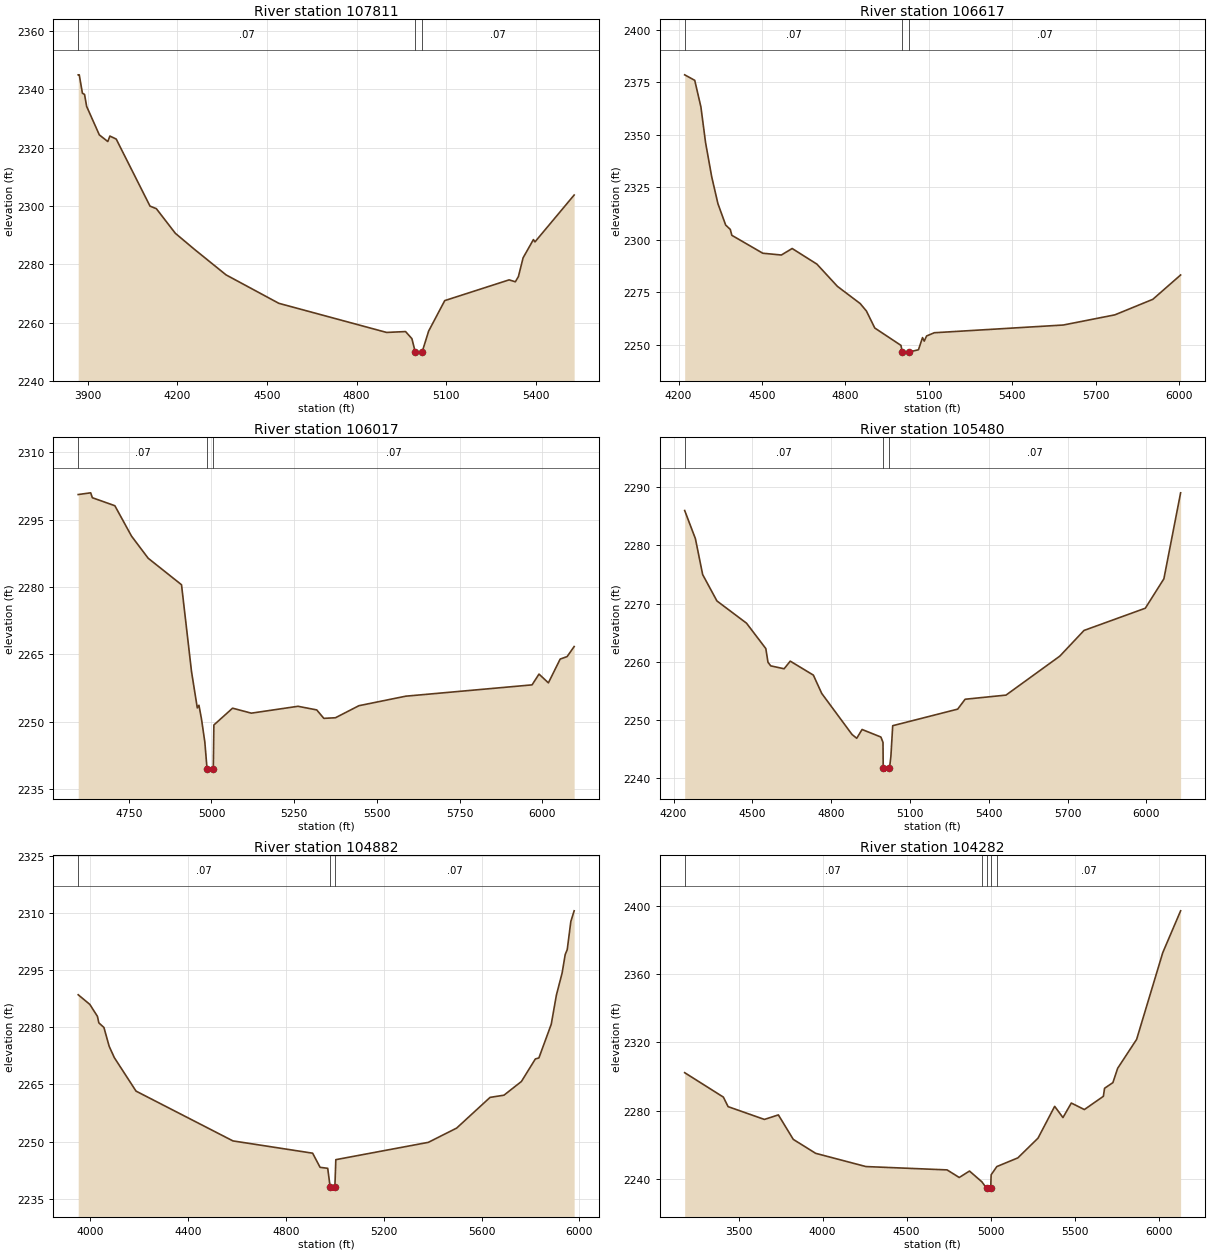
Type RM Length L Ch R = 1,107811,1194,1194,1194
BEGIN DESCRIPTION:
Bitter Creek 106.0
END DESCRIPTION:
XS GIS Cut Line= 3
      1424854.98      6811637.98      1425645.35      6812448.81
      1426154.98      6812587.99
#Sta/Elev= 30
  3867.7 2344.91  3871.2 2344.91  3881.8 2338.60  3888.9 2338.20  3895.9 2334.10
  3938.4 2324.33  3966.7 2322.05  3973.8 2323.92  3994.9 2322.90  4108.1 2299.92
  4129.4 2299.03  4193.0 2290.59  4256.7 2285.12  4362.7 2276.35  4539.5 2266.60
  4900.3 2256.62  4963.8 2256.92  4985.0 2254.49  4996.0 2250.03  4996.5 2249.53
  5019.6 2250.03  5041.1 2257.09  5095.0 2267.53  5310.6 2274.64  5331.4 2273.98
  5341.7 2275.78  5357.4 2282.21  5391.9 2288.45  5397.1 2287.65  5528.3 2303.72
#Mann=3,-1,0
  3867.7    0.07       0  4996.0    0.07       0  5019.6    0.07       0
Bank Sta=4996,5019.6
Exp/Cntr=0.3,0.1

Type RM Length L Ch R = 1,106617,600,600,600
BEGIN DESCRIPTION:
Bitter Creek 105.0
END DESCRIPTION:
XS GIS Cut Line= 3
      1424505.04      6812838.02      1425198.88      6813190.18
      1426005.00      6812588.00
#Sta/Elev= 30
  4221.9 2378.56  4258.1 2375.94  4280.3 2363.26  4297.0 2346.32  4319.2 2329.96
  4341.5 2317.20  4369.4 2306.99  4386.0 2304.91  4391.6 2302.11  4502.9 2293.57
  4569.7 2292.72  4608.6 2295.82  4697.7 2288.38  4771.4 2277.79  4853.5 2269.58
  4875.8 2266.04  4905.9 2257.94  5000.0 2249.68  5005.1 2246.48  5005.6 2245.98
  5028.7 2246.48  5063.0 2247.59  5077.6 2253.37  5083.8 2251.70  5092.2 2254.15
  5120.0 2255.69  5584.1 2259.37  5769.6 2264.21  5906.3 2271.62  6006.2 2283.21
#Mann=3,-1,0
  4221.9    0.07       0  5005.1    0.07       0  5028.7    0.07       0
Bank Sta=5005.1,5028.7
Exp/Cntr=0.3,0.1

Type RM Length L Ch R = 1,106017,537,537,537
BEGIN DESCRIPTION:
Bitter Creek 104.0
END DESCRIPTION:
XS GIS Cut Line= 3
      1424655.04      6813688.00      1425054.92      6813738.04
      1425855.02      6812987.98
#Sta/Elev= 30
  4597.0 2300.60  4634.7 2300.98  4639.8 2299.89  4707.8 2298.11  4758.2 2291.34
  4808.6 2286.41  4909.4 2280.51  4939.6 2261.19  4957.1 2253.08  4962.1 2253.67
  4969.8 2250.61  4979.9 2245.48  4986.6 2239.50  4987.0 2239.00  5005.5 2239.50
  5007.2 2249.27  5063.8 2253.02  5120.5 2251.91  5261.7 2253.44  5318.3 2252.63
  5339.8 2250.75  5375.0 2250.89  5445.8 2253.57  5587.4 2255.69  5969.4 2258.21
  5990.4 2260.61  6018.8 2258.66  6054.4 2263.95  6075.4 2264.51  6096.7 2266.74
#Mann=3,-1,0
  4597.0    0.07       0  4986.6    0.07       0  5005.5    0.07       0
Bank Sta=4986.6,5005.5
Exp/Cntr=0.3,0.1

Type RM Length L Ch R = 1,105480,598,598,598
BEGIN DESCRIPTION:
Bitter Creek 103.0
END DESCRIPTION:
XS GIS Cut Line= 3
      1424705.03      6814137.99      1425445.50      6813976.84
      1426255.01      6813187.99
#Sta/Elev= 30
  4242.2 2286.01  4283.1 2281.16  4310.7 2274.99  4365.0 2270.46  4477.6 2266.64
  4551.1 2262.27  4559.4 2259.92  4569.7 2259.30  4620.8 2258.80  4644.1 2260.11
  4732.1 2257.71  4764.1 2254.55  4879.4 2247.50  4897.2 2246.85  4917.6 2248.36
  4989.3 2247.06  4997.2 2246.14  4998.1 2241.70  4998.6 2241.20  5021.9 2241.70
  5027.2 2243.69  5034.2 2249.01  5281.6 2251.86  5309.9 2253.56  5465.5 2254.27
  5670.6 2260.98  5762.6 2265.39  5995.9 2269.21  6066.6 2274.27  6130.3 2289.05
#Mann=3,-1,0
  4242.2    0.07       0  4998.1    0.07       0  5021.9    0.07       0
Bank Sta=4998.1,5021.9
Exp/Cntr=0.3,0.1

Type RM Length L Ch R = 1,104882,600,600,600
BEGIN DESCRIPTION:
Bitter Creek 102.0
END DESCRIPTION:
XS GIS Cut Line= 4
      1424654.95      6814187.98      1425527.15      6814480.51
      1425653.24      6814449.88      1426454.96      6813888.03
#Sta/Elev= 30
  3950.3 2288.54  3997.7 2286.02  4029.0 2282.87  4034.7 2281.17  4055.5 2279.96
  4076.9 2275.03  4098.0 2272.05  4186.9 2263.26  4583.2 2250.20  4909.2 2246.98
  4939.7 2243.27  4970.9 2243.01  4981.1 2238.05  4981.5 2237.55  5000.2 2238.05
  5004.1 2245.28  5382.4 2249.82  5498.3 2253.56  5635.1 2261.62  5691.8 2262.19
  5763.3 2265.79  5820.3 2271.70  5834.8 2271.97  5885.3 2280.80  5906.3 2288.44
  5929.8 2294.25  5942.4 2299.10  5950.7 2300.38  5965.5 2307.78  5979.0 2310.56
#Mann=3,-1,0
  3950.3    0.07       0  4981.1    0.07       0  5000.2    0.07       0
Bank Sta=4981.1,5000.2
Exp/Cntr=0.3,0.1

Type RM Length L Ch R = 1,104282,591,591,591
BEGIN DESCRIPTION:
Bitter Creek 101.0
END DESCRIPTION:
XS GIS Cut Line= 3
      1424204.97      6814137.98      1425825.59      6814968.42
      1426604.99      6815787.99
#Sta/Elev= 30
  3179.0 2302.25  3409.3 2287.97  3437.5 2282.39  3653.5 2274.91  3736.7 2277.55
  3825.5 2263.23  3958.7 2255.08  4257.7 2247.34  4740.9 2245.39  4813.3 2240.95
  4874.3 2244.72  4948.3 2238.39  4976.2 2234.64  4976.7 2234.14  5000.7 2234.64
  5003.2 2242.54  5037.1 2247.34  5162.1 2252.41  5282.2 2263.96  5381.3 2282.56
  5430.7 2276.00  5480.4 2284.49  5558.1 2280.69  5671.3 2288.43  5678.2 2293.12
  5727.9 2296.44  5756.2 2304.81  5869.1 2321.73  6024.8 2372.48  6131.0 2396.92
#Mann=5,-1,0
  3179.0    0.07       0  4948.3    0.16       0  4976.2    0.07       0
  5000.7    0.16       0  5037.1    0.07       0
Bank Sta=4976.2,5000.7
Exp/Cntr=0.3,0.1

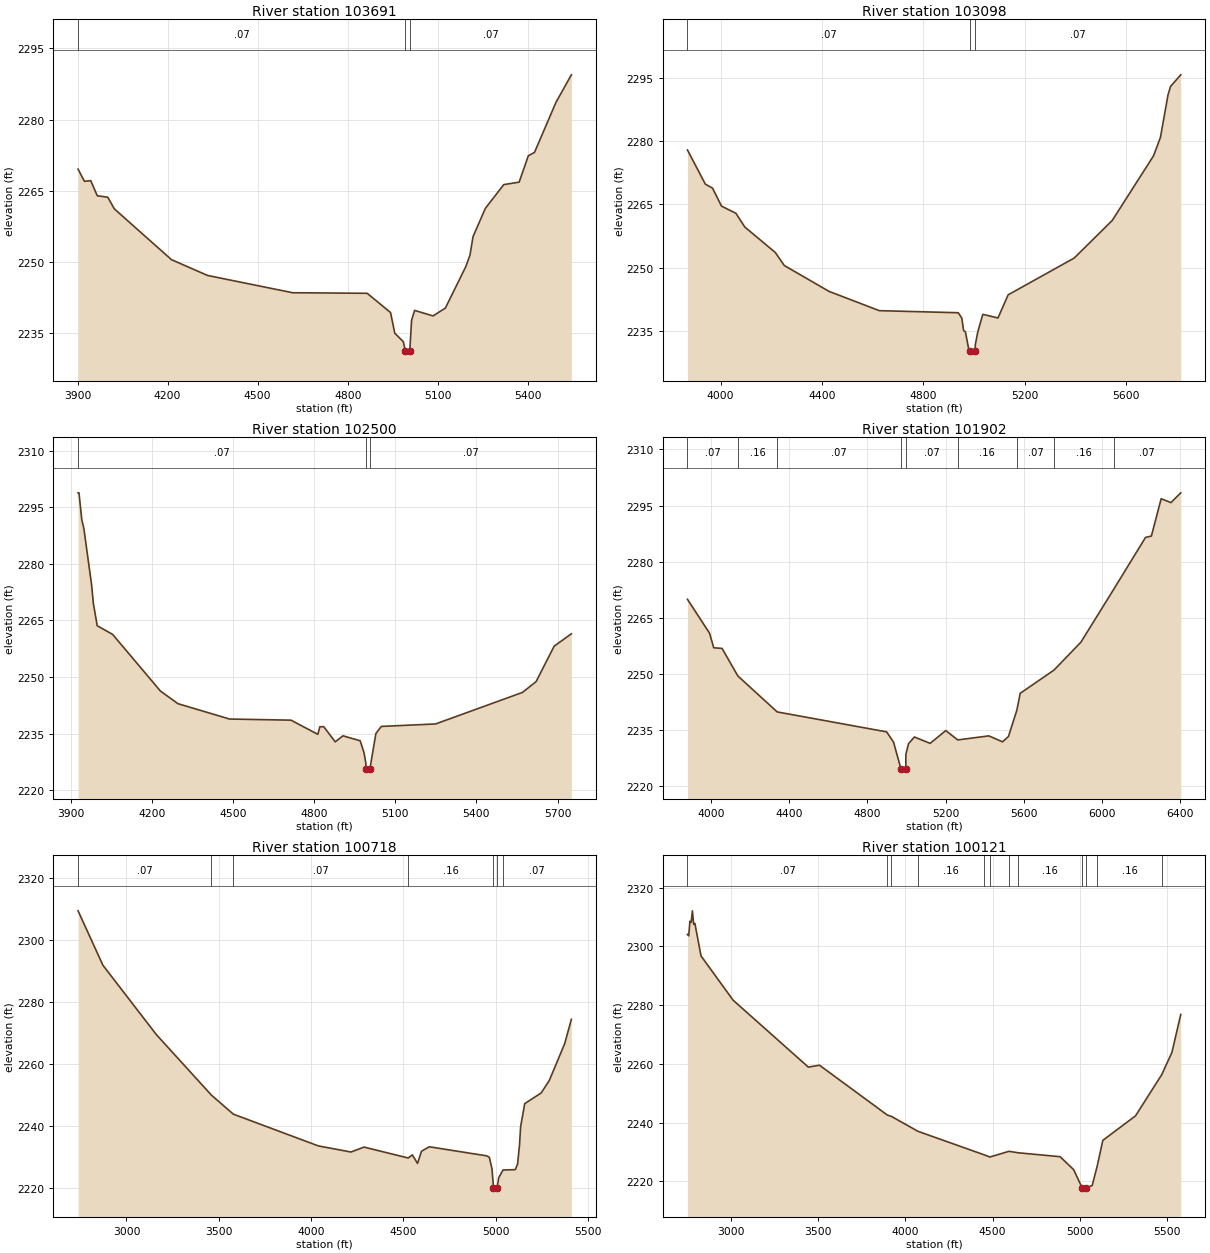
Type RM Length L Ch R = 1,103691,593,593,593
BEGIN DESCRIPTION:
Bitter Creek 100.0
END DESCRIPTION:
XS GIS Cut Line= 3
      1424655.03      6814488.03      1425472.53      6815221.34
      1426005.00      6815338.00
#Sta/Elev= 30
  3901.8 2269.54  3923.1 2266.97  3944.0 2267.12  3965.7 2263.93  4000.8 2263.62
  4022.5 2261.17  4213.1 2250.44  4333.5 2247.11  4616.8 2243.47  4865.0 2243.35
  4942.7 2239.30  4956.9 2234.93  4985.3 2233.15  4992.1 2231.23  4992.4 2230.73
  5006.8 2231.23  5012.8 2237.66  5023.0 2239.74  5084.4 2238.58  5125.4 2240.24
  5193.3 2248.96  5207.3 2251.40  5217.5 2255.30  5258.5 2261.26  5319.9 2266.28
  5371.1 2266.80  5401.8 2272.37  5422.3 2273.07  5493.9 2283.64  5545.1 2289.44
#Mann=3,-1,0
  3901.8    0.07       0  4992.1    0.07       0  5006.8    0.07       0
Bank Sta=4992.1,5006.8
Exp/Cntr=0.3,0.1

Type RM Length L Ch R = 1,103098,598,598,598
BEGIN DESCRIPTION:
Bitter Creek 99.0
END DESCRIPTION:
XS GIS Cut Line= 3
      1424354.99      6814837.99      1425140.86      6815650.81
      1425955.01      6815688.00
#Sta/Elev= 30
  3869.4 2277.96  3940.0 2269.83  3968.3 2268.88  4003.8 2264.60  4060.4 2262.91
  4095.7 2259.63  4216.0 2253.57  4251.3 2250.48  4428.0 2244.32  4626.1 2239.74
  4937.4 2239.25  4951.5 2237.97  4958.5 2235.02  4965.7 2234.70  4979.8 2230.26
  4984.9 2230.14  4985.3 2229.64  5004.5 2230.14  5004.6 2231.61  5014.2 2234.60
  5034.2 2238.86  5094.2 2238.01  5134.3 2243.51  5394.6 2252.25  5544.7 2261.19
  5707.6 2276.56  5734.9 2280.96  5764.9 2291.11  5774.9 2293.09  5815.0 2295.84
#Mann=3,-1,0
  3869.4    0.07       0  4984.9    0.07       0  5004.5    0.07       0
Bank Sta=4984.9,5004.5
Exp/Cntr=0.3,0.1

Type RM Length L Ch R = 1,102500,598,598,598
BEGIN DESCRIPTION:
Bitter Creek 98.0
END DESCRIPTION:
XS GIS Cut Line= 3
      1424154.98      6815337.97      1424856.56      6816148.64
      1425605.00      6816088.00
#Sta/Elev= 30
  3927.9 2298.83  3931.2 2298.83  3941.7 2291.67  3949.3 2289.36  3977.8 2274.49
  3984.4 2269.48  3998.7 2263.59  4055.7 2261.29  4232.3 2246.28  4297.0 2242.93
  4487.8 2238.86  4714.9 2238.56  4814.0 2234.80  4821.3 2236.79  4835.5 2236.85
  4878.3 2232.81  4906.6 2234.41  4970.4 2233.10  4984.6 2229.93  4991.3 2227.24
  4991.5 2225.55  4991.8 2225.05  5006.2 2225.55  5028.5 2235.02  5048.6 2236.90
  5249.3 2237.56  5570.3 2245.92  5620.5 2248.77  5687.3 2258.17  5750.9 2261.46
#Mann=3,-1,0
  3927.9    0.07       0  4991.5    0.07       0  5006.2    0.07       0
Bank Sta=4991.5,5006.2
Exp/Cntr=0.3,0.1

Type RM Length L Ch R = 1,101902,1184,1184,1184
BEGIN DESCRIPTION:
Bitter Creek 97.0
END DESCRIPTION:
XS GIS Cut Line= 3
      1423855.03      6815888.03      1424654.00      6816672.06
      1426054.95      6816738.00
#Sta/Elev= 30
  3880.6 2269.95  3993.6 2260.89  4014.9 2257.00  4057.4 2256.83  4138.3 2249.46
  4339.3 2239.86  4898.9 2234.53  4934.2 2231.78  4972.5 2224.54  4973.0 2224.04
  4997.1 2224.54  4997.2 2228.51  5011.0 2231.40  5041.0 2233.16  5121.1 2231.46
  5201.2 2234.87  5262.3 2232.38  5421.5 2233.46  5491.5 2231.87  5521.6 2233.29
  5564.8 2240.35  5581.6 2244.82  5754.3 2251.03  5892.0 2258.49  6060.1 2272.65
  6222.4 2286.48  6252.4 2286.85  6302.4 2296.83  6352.5 2295.79  6402.5 2298.40
#Mann=9,-1,0
  3880.6    0.07       0  4138.3    0.16       0  4339.3    0.07       0
  4972.5    0.07       0  4997.1    0.07       0  5262.3    0.16       0
  5564.8    0.07       0  5754.3    0.16       0  6060.1    0.07       0
Bank Sta=4972.5,4997.1
Exp/Cntr=0.3,0.1

Type RM Length L Ch R = 1,100718,597,597,597
BEGIN DESCRIPTION:
Bitter Creek 96.0
END DESCRIPTION:
XS GIS Cut Line= 3
      1423454.98      6815687.98      1425040.74      6817301.33
      1425405.00      6817488.00
#Sta/Elev= 30
  2737.8 2309.45  2872.2 2291.91  3162.1 2269.50  3460.3 2249.99  3578.7 2243.87
  4039.0 2233.63  4215.7 2231.66  4286.4 2233.25  4525.8 2229.73  4548.0 2230.74
  4576.3 2227.98  4597.6 2231.92  4640.0 2233.35  4951.2 2230.42  4965.3 2229.95
  4979.5 2226.19  4987.6 2220.19  4988.0 2219.69  5007.3 2220.19  5016.0 2223.37
  5039.1 2225.85  5105.9 2225.98  5118.0 2227.78  5128.4 2233.80  5134.6 2239.88
  5156.8 2247.27  5245.6 2250.70  5290.0 2254.76  5373.2 2266.61  5409.3 2274.45
#Mann=7,-1,0
  2737.8    0.07       0  3460.3    0.16       0  3578.7    0.07       0
  4525.8    0.16       0  4987.6    0.07       0  5007.3    0.16       0
  5039.1    0.07       0
Bank Sta=4987.6,5007.3
Exp/Cntr=0.3,0.1

Type RM Length L Ch R = 1,100121,590,590,590
BEGIN DESCRIPTION:
Bitter Creek 95.0
END DESCRIPTION:
XS GIS Cut Line= 3
      1423204.97      6816037.97      1424784.92      6817637.81
      1425354.98      6817738.00
#Sta/Elev= 30
  2751.5 2304.07  2758.6 2303.61  2765.6 2308.54  2772.8 2308.20  2779.8 2312.10
  2786.9 2307.50  2793.9 2307.83  2829.3 2296.74  3013.2 2281.68  3444.5 2258.90
  3508.2 2259.56  3897.1 2242.59  3920.8 2242.12  4072.9 2237.05  4452.8 2229.04
  4484.8 2228.32  4594.3 2230.25  4647.2 2229.75  4887.1 2228.42  4964.8 2224.02
  5013.1 2217.88  5013.6 2217.38  5037.8 2217.88  5071.2 2218.60  5100.1 2225.26
  5132.1 2233.98  5319.4 2242.31  5469.2 2256.28  5528.1 2263.89  5578.8 2276.83
#Mann=12,-1,0
  2751.5    0.07       0  3897.1    0.16       0  3920.8    0.07       0
  4072.9    0.16       0  4452.8    0.07       0  4484.8    0.16       0
  4594.3    0.07       0  4647.2    0.16       0  5013.1    0.07       0
  5037.8    0.16       0  5100.1    0.16       0  5469.2    0.07       0
Bank Sta=5013.1,5037.8
Exp/Cntr=0.3,0.1