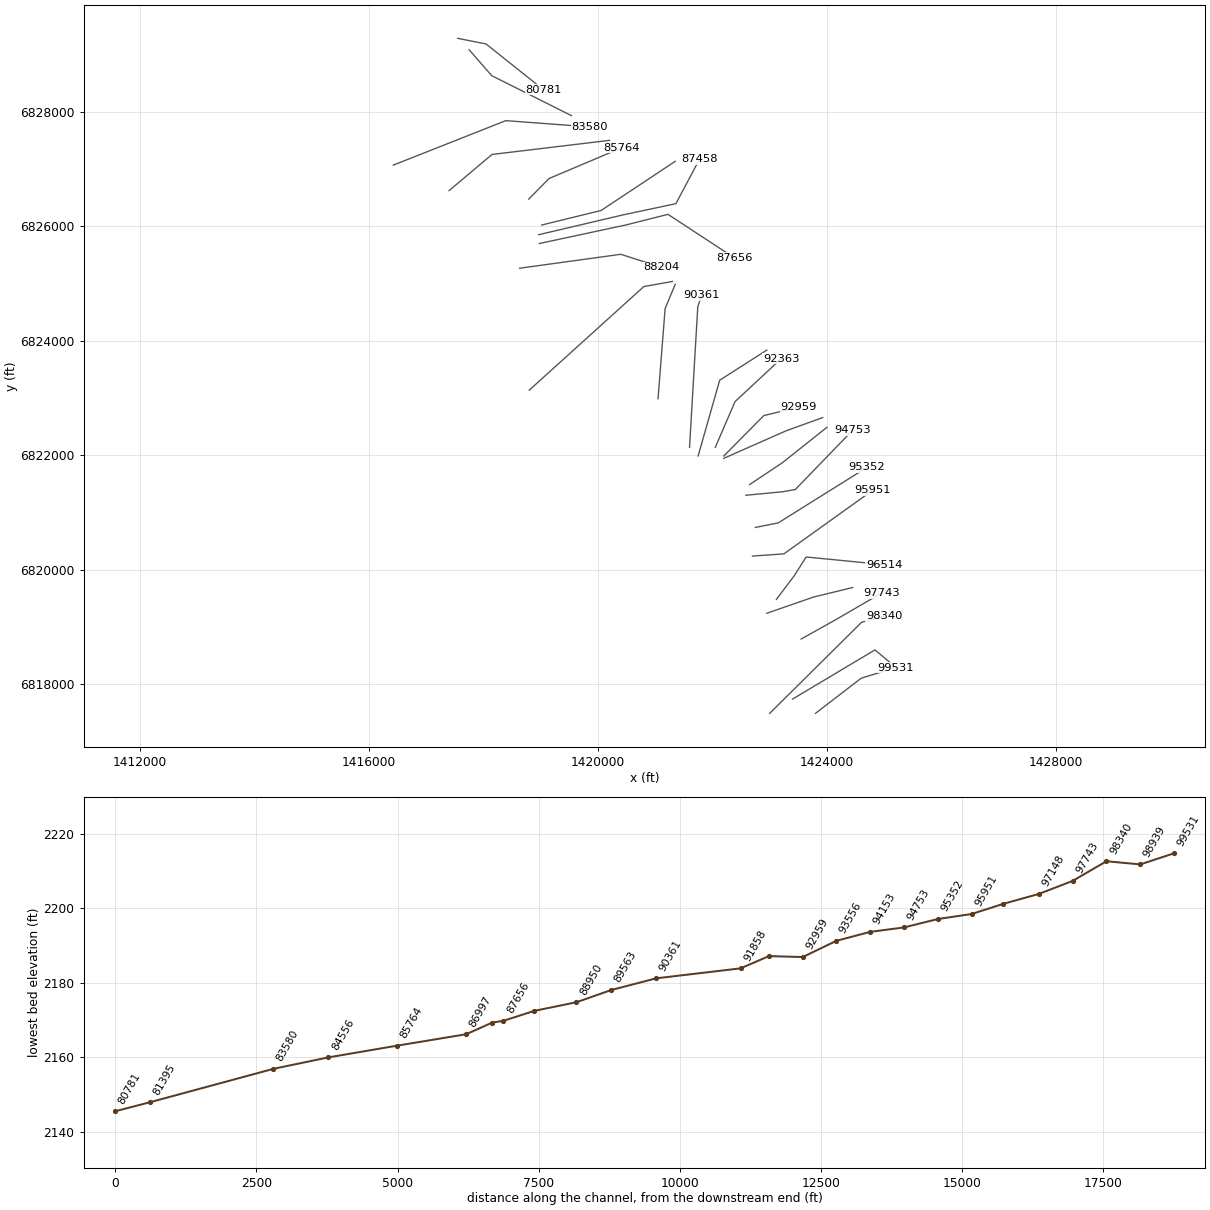
HEC-RAS study Bitter Creek.prj: Bitter Creek Base Level Engineering

--- Bitter Creek.g01 (geometry) --- (continued)

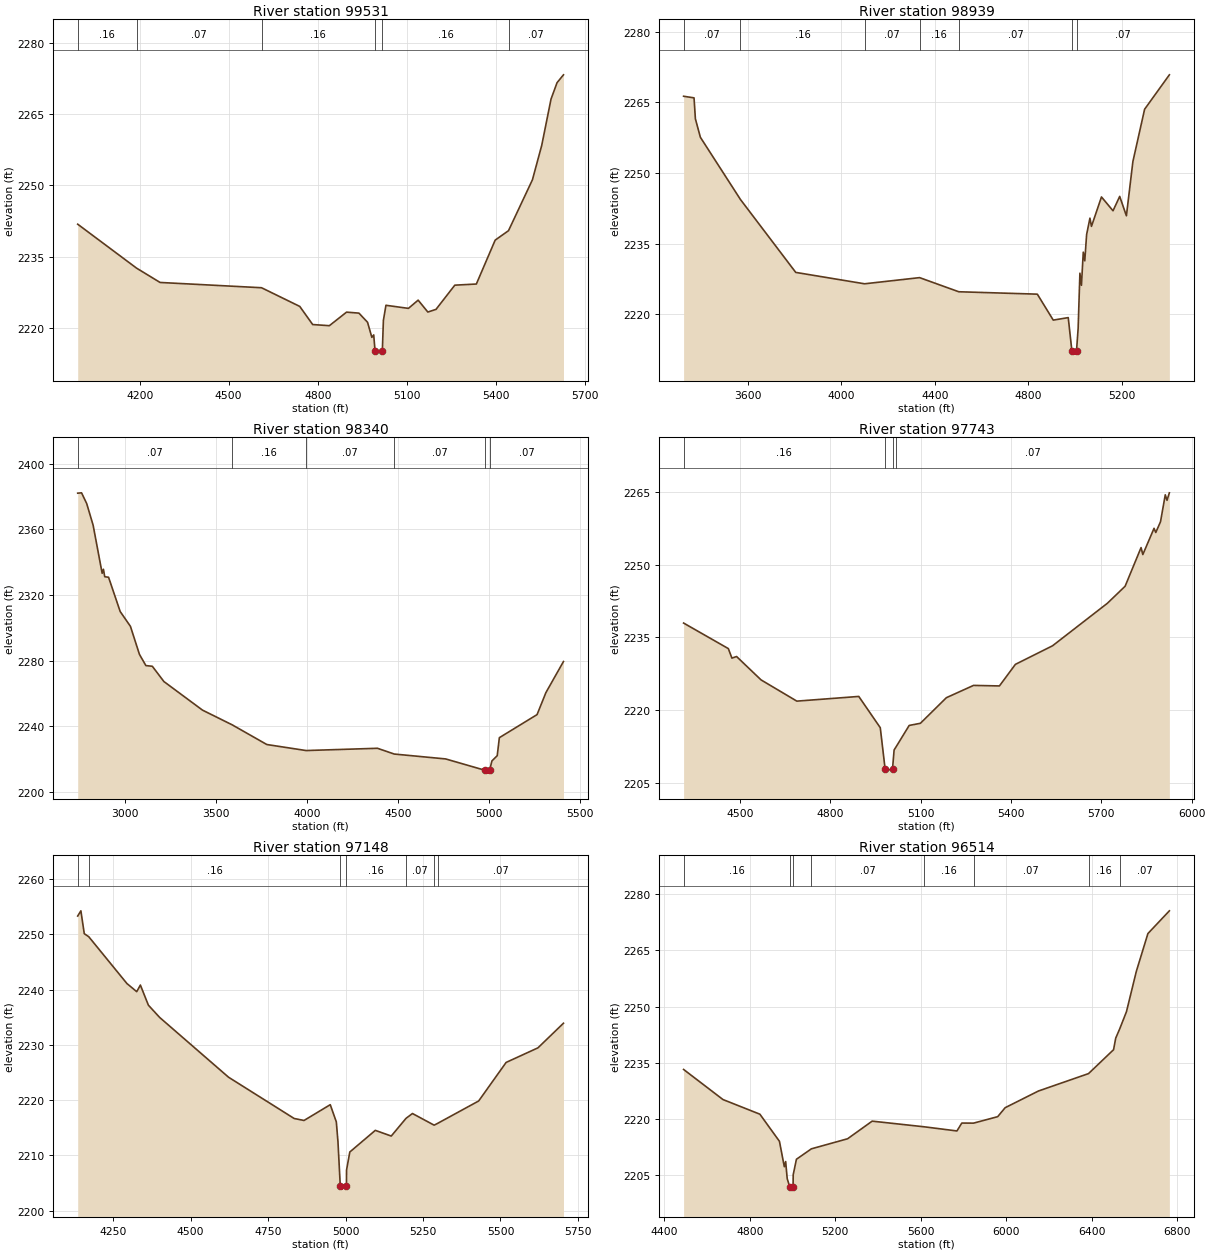
Type RM Length L Ch R = 1,99531,592,592,592
BEGIN DESCRIPTION:
Bitter Creek 94.0
END DESCRIPTION:
XS GIS Cut Line= 3
      1423805.01      6817488.00      1424604.51      6818103.20
      1425205.02      6818288.01
#Sta/Elev= 30
  3991.2 2241.83  4189.6 2232.59  4268.8 2229.58  4610.7 2228.47  4739.6 2224.54
  4783.1 2220.73  4839.3 2220.49  4897.3 2223.34  4939.0 2223.13  4968.0 2221.21
  4982.5 2218.04  4988.8 2218.55  4993.2 2215.22  4993.7 2214.72  5017.9 2215.22
  5021.4 2221.59  5030.0 2224.78  5105.8 2224.13  5138.5 2225.86  5171.2 2223.36
  5198.7 2223.92  5262.1 2229.01  5334.7 2229.25  5398.1 2238.48  5443.1 2240.47
  5523.7 2251.17  5555.0 2258.40  5586.4 2268.15  5606.7 2271.59  5628.3 2273.24
#Mann=6,-1,0
  3991.2    0.16       0  4189.6    0.07       0  4610.7    0.16       0
  4993.2    0.07       0  5017.9    0.16       0  5443.1    0.07       0
Bank Sta=4993.2,5017.9
Exp/Cntr=0.3,0.1

Type RM Length L Ch R = 1,98939,599,599,599
BEGIN DESCRIPTION:
Bitter Creek 93.0
END DESCRIPTION:
XS GIS Cut Line= 3
      1423405.04      6817738.02      1424844.15      6818597.64
      1425154.98      6818338.01
#Sta/Elev= 30
  3323.7 2266.31  3368.4 2265.97  3374.2 2261.52  3395.6 2257.60  3567.3 2244.39
  3804.2 2228.91  4099.1 2226.49  4334.8 2227.80  4502.6 2224.80  4839.3 2224.29
  4907.5 2218.78  4971.7 2219.31  4987.3 2212.27  4987.7 2211.77  5007.2 2212.27
  5014.1 2216.99  5021.7 2228.74  5028.3 2226.17  5036.1 2233.21  5042.6 2231.36
  5050.4 2236.94  5064.7 2240.43  5071.2 2238.68  5114.1 2244.93  5163.6 2241.99
  5192.2 2245.05  5220.9 2240.93  5248.7 2252.44  5298.9 2263.55  5405.0 2270.86
#Mann=7,-1,0
  3323.7    0.07       0  3567.3    0.16       0  4099.1    0.07       0
  4334.8    0.16       0  4502.6    0.07       0  4987.3    0.07       0
  5007.2    0.07       0
Bank Sta=4987.3,5007.2
Exp/Cntr=0.3,0.1

Type RM Length L Ch R = 1,98340,597,597,597
BEGIN DESCRIPTION:
Bitter Creek 92.0
END DESCRIPTION:
XS GIS Cut Line= 3
      1423004.99      6817487.99      1424610.93      6819080.26
      1425004.97      6819187.99
#Sta/Elev= 30
  2738.5 2382.00  2759.7 2382.21  2788.0 2375.65  2823.3 2362.46  2872.9 2333.19
  2879.9 2335.63  2887.0 2331.10  2908.2 2330.75  2971.9 2309.90  3028.4 2300.84
  3077.9 2283.76  3113.3 2276.93  3148.6 2276.52  3212.3 2267.21  3424.4 2249.79
  3587.4 2240.84  3778.0 2228.83  3994.0 2225.16  4386.1 2226.54  4478.3 2223.03
  4760.9 2220.05  4977.6 2213.12  4978.1 2212.62  5002.4 2213.12  5015.1 2218.82
  5044.4 2222.03  5056.1 2233.00  5263.4 2247.07  5311.9 2260.46  5408.5 2279.41
#Mann=6,-1,0
  2738.5    0.07       0  3587.4    0.16       0  3994.0    0.07       0
  4478.3    0.07       0  4977.6    0.07       0  5002.4    0.07       0
Bank Sta=4977.6,5002.4
Exp/Cntr=0.3,0.1

Type RM Length L Ch R = 1,97743,595,595,595
BEGIN DESCRIPTION:
Bitter Creek 91.0
END DESCRIPTION:
XS GIS Cut Line= 3
      1423554.98      6818787.99      1424154.35      6819122.72
      1424954.98      6819587.99
#Sta/Elev= 30
  4313.5 2237.97  4462.0 2232.69  4473.9 2230.72  4489.4 2231.05  4570.6 2226.22
  4689.4 2221.83  4895.0 2222.80  4966.4 2216.33  4982.3 2207.86  4982.8 2207.36
  5007.1 2207.86  5012.3 2211.74  5020.2 2212.52  5062.3 2216.80  5099.6 2217.25
  5185.8 2222.54  5275.9 2225.08  5361.9 2224.97  5414.9 2229.43  5538.2 2233.27
  5720.3 2242.06  5779.1 2245.58  5832.1 2253.57  5837.9 2252.13  5875.1 2257.55
  5880.9 2256.69  5896.6 2258.91  5912.4 2264.48  5918.2 2263.34  5926.0 2264.89
#Mann=4,-1,0
  4313.5    0.16       0  4982.3    0.07       0  5007.1    0.16       0
  5020.2    0.07       0
Bank Sta=4982.3,5007.1
Exp/Cntr=0.3,0.1

Type RM Length L Ch R = 1,97148,634,634,634
BEGIN DESCRIPTION:
Bitter Creek 90.0
END DESCRIPTION:
XS GIS Cut Line= 3
      1422955.01      6819238.00      1423771.71      6819521.51
      1424455.01      6819688.00
#Sta/Elev= 30
  4135.5 2253.33  4145.8 2254.27  4156.7 2250.13  4171.2 2249.58  4294.3 2241.11
  4326.0 2239.63  4337.8 2240.83  4363.6 2237.19  4400.1 2234.96  4622.4 2224.14
  4834.1 2216.67  4865.9 2216.31  4950.6 2219.17  4970.2 2216.05  4975.5 2212.46
  4983.0 2204.38  4983.4 2203.88  5002.9 2204.38  5003.1 2207.32  5013.7 2210.60
  5096.0 2214.52  5147.5 2213.49  5195.2 2216.70  5215.9 2217.57  5285.9 2215.46
  5297.6 2215.80  5429.6 2219.84  5518.2 2226.82  5620.9 2229.46  5703.3 2233.92
#Mann=7,-1,0
  4135.5    0.07       0  4171.2    0.16       0  4983.0    0.07       0
  5002.9    0.16       0  5195.2    0.07       0  5285.9    0.16       0
  5297.6    0.07       0
Bank Sta=4983,5002.9
Exp/Cntr=0.3,0.1

Type RM Length L Ch R = 1,96514,563,563,563
BEGIN DESCRIPTION:
Bitter Creek 89.0
END DESCRIPTION:
XS GIS Cut Line= 4
      1423122.72      6819480.75      1423430.11      6819888.08
      1423642.75      6820221.50      1425004.97      6820088.00
#Sta/Elev= 30
  4489.7 2233.19  4674.2 2225.14  4846.9 2221.23  4938.5 2213.98  4961.3 2207.19
  4967.6 2208.57  4974.8 2204.01  4987.1 2201.70  4987.4 2201.20  5002.2 2201.70
  5002.9 2205.04  5018.0 2209.18  5088.0 2211.97  5257.5 2214.66  5372.6 2219.37
  5616.1 2217.86  5769.5 2216.75  5792.4 2218.86  5847.4 2218.84  5960.4 2220.57
  5995.4 2222.97  6151.3 2227.43  6385.7 2232.08  6502.9 2238.47  6513.0 2241.56
  6531.5 2244.01  6563.3 2248.63  6609.5 2259.41  6663.7 2269.51  6764.2 2275.59
#Mann=8,-1,0
  4489.7    0.16       0  4987.1    0.07       0  5002.2    0.16       0
  5088.0    0.07       0  5616.1    0.16       0  5847.4    0.07       0
  6385.7    0.16       0  6531.5    0.07       0
Bank Sta=4987.1,5002.2
Exp/Cntr=0.3,0.1

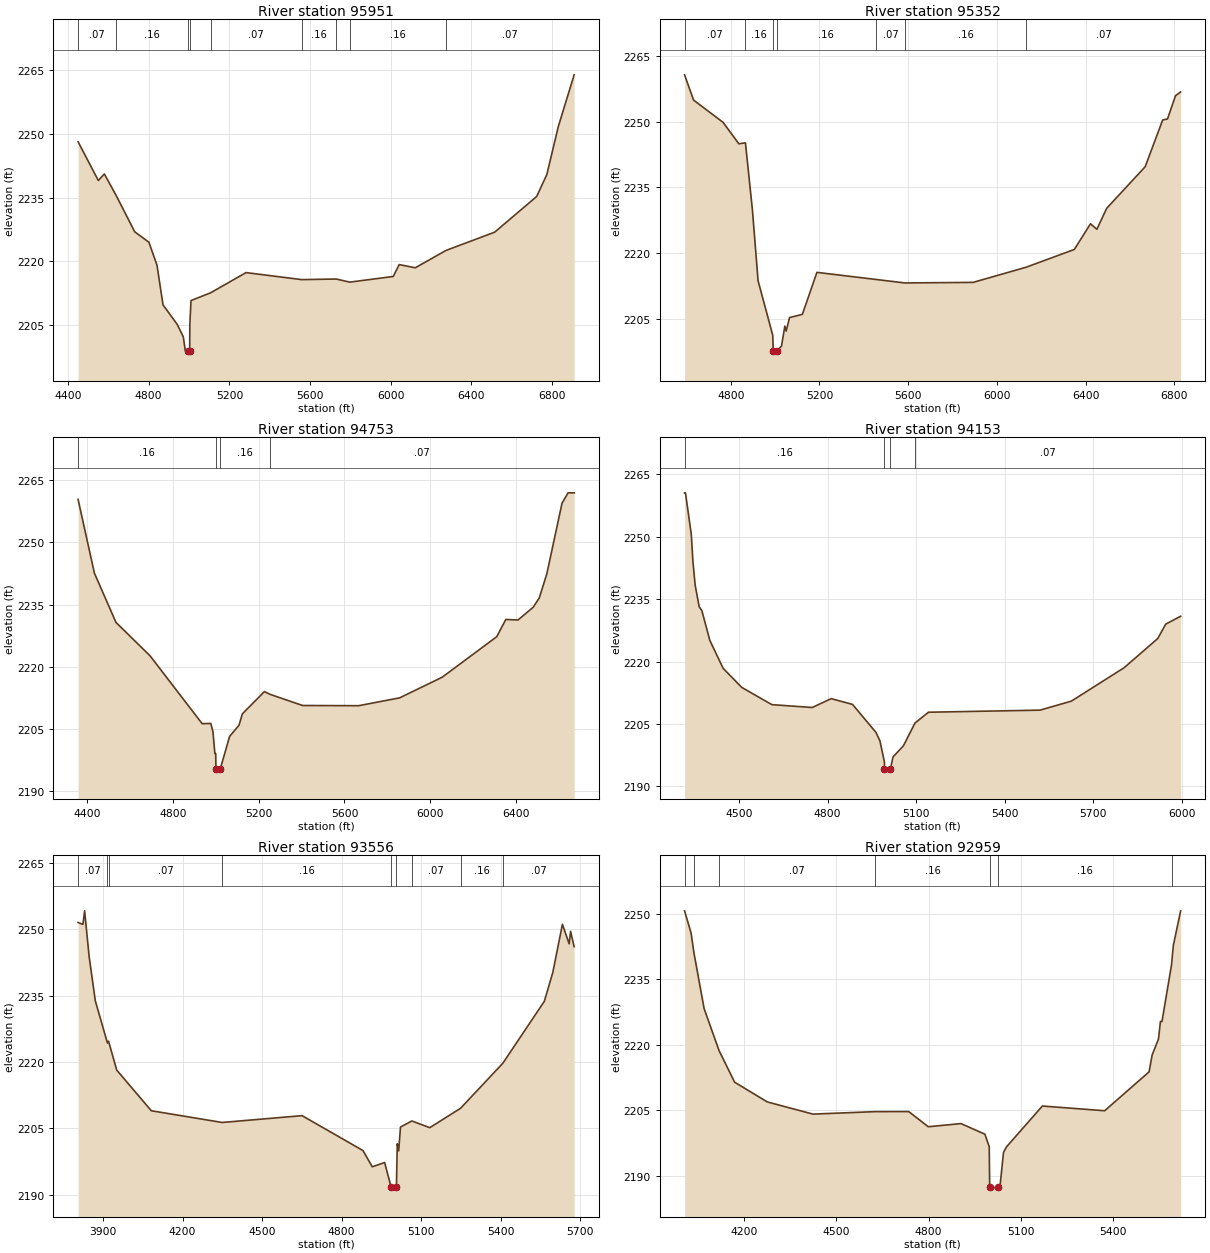
Type RM Length L Ch R = 1,95951,599,599,599
BEGIN DESCRIPTION:
Bitter Creek 88.0
END DESCRIPTION:
XS GIS Cut Line= 3
      1422704.99      6820238.00      1423253.47      6820276.12
      1424805.00      6821388.00
#Sta/Elev= 30
  4450.2 2248.10  4550.4 2239.01  4580.5 2240.54  4640.4 2235.35  4730.9 2226.96
  4801.1 2224.51  4841.1 2219.16  4871.2 2209.80  4941.4 2205.23  4971.5 2202.32
  4981.5 2199.05  4993.3 2198.97  4993.5 2198.47  5003.3 2198.97  5004.0 2205.22
  5009.9 2210.82  5106.9 2212.63  5282.6 2217.38  5558.4 2215.73  5729.5 2215.87
  5796.8 2215.14  6012.2 2216.47  6041.7 2219.26  6121.4 2218.51  6273.6 2222.58
  6515.1 2226.88  6723.3 2235.26  6773.5 2240.42  6830.2 2251.65  6908.8 2263.82
#Mann=9,-1,0
  4450.2    0.07       0  4640.4    0.16       0  4993.3    0.07       0
  5003.3    0.16       0  5106.9    0.07       0  5558.4    0.16       0
  5729.5    0.07       0  5796.8    0.16       0  6273.6    0.07       0
Bank Sta=4993.3,5003.3
Exp/Cntr=0.3,0.1

Type RM Length L Ch R = 1,95352,599,599,599
BEGIN DESCRIPTION:
Bitter Creek 87.0
END DESCRIPTION:
XS GIS Cut Line= 3
      1422754.99      6820738.00      1423155.07      6820817.97
      1424705.04      6821788.03
#Sta/Elev= 30
  4592.0 2260.73  4632.8 2254.95  4765.4 2249.88  4836.8 2244.97  4866.5 2245.18
  4897.9 2229.88  4923.5 2213.66  4989.7 2201.19  4991.7 2197.62  4992.0 2197.12
  5006.8 2197.62  5028.9 2198.70  5044.2 2203.30  5050.1 2202.17  5065.4 2205.25
  5123.2 2205.98  5188.7 2215.58  5455.9 2213.95  5585.2 2213.16  5893.0 2213.29
  6131.7 2216.75  6349.2 2220.81  6422.3 2226.69  6450.9 2225.42  6495.4 2230.23
  6668.7 2239.72  6747.7 2250.41  6769.5 2250.64  6805.5 2255.96  6828.5 2256.81
#Mann=7,-1,0
  4592.0    0.07       0  4866.5    0.16       0  4991.7    0.07       0
  5006.8    0.16       0  5455.9    0.07       0  5585.2    0.16       0
  6131.7    0.07       0
Bank Sta=4991.7,5006.8
Exp/Cntr=0.3,0.1

Type RM Length L Ch R = 1,94753,600,600,600
BEGIN DESCRIPTION:
Bitter Creek 86.0
END DESCRIPTION:
XS GIS Cut Line= 4
      1422589.24      6821301.14      1423227.89      6821361.50
      1423452.95      6821400.97      1424455.03      6822438.03
#Sta/Elev= 30
  4358.5 2260.32  4434.6 2242.55  4535.0 2230.70  4693.9 2222.65  4936.8 2206.30
  4977.0 2206.36  4987.1 2204.37  4996.0 2199.10  5000.0 2199.10  5001.0 2195.37
  5001.4 2194.87  5021.0 2195.37  5064.8 2203.24  5108.7 2205.94  5124.2 2208.67
  5227.0 2214.03  5253.5 2213.36  5404.8 2210.68  5666.4 2210.63  5857.3 2212.52
  6055.3 2217.48  6309.8 2227.25  6352.2 2231.41  6408.8 2231.27  6479.6 2234.34
  6507.8 2236.56  6543.3 2242.40  6614.1 2259.40  6642.4 2261.91  6670.6 2261.90
#Mann=4,-1,0
  4358.5    0.16       0  5001.0    0.07       0  5021.0    0.16       0
  5253.5    0.07       0
Bank Sta=5001,5021
Exp/Cntr=0.3,0.1

Type RM Length L Ch R = 1,94153,597,597,597
BEGIN DESCRIPTION:
Bitter Creek 85.0
END DESCRIPTION:
XS GIS Cut Line= 3
      1422654.98      6821487.99      1423224.65      6821867.85
      1424005.03      6822488.03
#Sta/Elev= 30
  4315.3 2260.58  4318.3 2260.58  4337.9 2250.74  4343.9 2243.86  4351.4 2238.32
  4364.9 2233.19  4373.9 2232.29  4400.9 2225.12  4446.0 2218.40  4509.1 2213.81
  4611.3 2209.66  4748.0 2208.98  4812.6 2211.10  4884.7 2209.72  4964.4 2202.96
  4977.8 2200.90  4992.8 2195.88  4993.0 2194.18  4993.4 2193.68  5013.0 2194.18
  5022.0 2197.09  5057.2 2199.77  5096.3 2205.23  5142.1 2207.84  5520.2 2208.34
  5626.3 2210.50  5805.2 2218.53  5919.1 2225.54  5946.3 2229.01  5996.8 2230.91
#Mann=4,-1,0
  4315.3    0.16       0  4993.0    0.07       0  5013.0    0.16       0
  5096.3    0.07       0
Bank Sta=4993,5013
Exp/Cntr=0.3,0.1

Type RM Length L Ch R = 1,93556,597,597,597
BEGIN DESCRIPTION:
Bitter Creek 84.0
END DESCRIPTION:
XS GIS Cut Line= 3
      1422202.52      6821945.94      1423294.45      6822428.48
      1423930.71      6822658.32
#Sta/Elev= 30
  3806.2 2251.48  3824.5 2251.07  3830.8 2254.12  3847.8 2243.81  3871.1 2233.81
  3916.8 2224.28  3921.0 2224.69  3951.9 2218.16  4082.2 2208.98  4349.4 2206.33
  4650.7 2207.87  4880.3 2199.99  4915.4 2196.32  4962.0 2197.29  4986.2 2191.78
  4986.6 2191.28  5006.4 2191.78  5009.6 2201.52  5014.9 2199.91  5021.8 2205.30
  5064.5 2206.67  5132.3 2205.16  5248.1 2209.53  5407.5 2219.69  5564.1 2233.69
  5596.0 2240.19  5632.3 2251.08  5657.7 2246.67  5663.0 2249.49  5676.5 2246.03
#Mann=9,-1,0
  3806.2    0.07       0  3916.8    0.16       0  3921.0    0.07       0
  4349.4    0.16       0  4986.2    0.07       0  5006.4    0.16       0
  5064.5    0.07       0  5248.1    0.16       0  5407.5    0.07       0
Bank Sta=4986.2,5006.4
Exp/Cntr=0.3,0.1

Type RM Length L Ch R = 1,92959,596,596,596
BEGIN DESCRIPTION:
Bitter Creek 83.0
END DESCRIPTION:
XS GIS Cut Line= 3
      1422205.01      6821988.01      1422903.04      6822693.99
      1423504.96      6822837.99
#Sta/Elev= 30
  4007.2 2250.63  4028.4 2245.55  4037.8 2240.97  4070.8 2228.24  4119.2 2218.66
  4169.8 2211.41  4275.9 2206.89  4424.4 2204.10  4627.5 2204.67  4735.5 2204.68
  4799.1 2201.21  4905.2 2201.93  4983.0 2199.51  4997.1 2196.63  4998.6 2187.43
  4999.1 2186.93  5024.0 2187.43  5032.9 2188.13  5043.5 2195.34  5053.4 2196.62
  5169.7 2205.95  5372.2 2204.87  5516.4 2213.77  5526.4 2217.63  5547.0 2221.28
  5553.3 2225.30  5558.4 2225.30  5589.3 2238.22  5595.3 2242.72  5618.9 2250.59
#Mann=7,-1,0
  4007.2    0.07       0  4037.8    0.16       0  4119.2    0.07       0
  4627.5    0.16       0  4998.6    0.07       0  5024.0    0.16       0
  5589.3    0.07       0
Bank Sta=4998.6,5024
Exp/Cntr=0.3,0.1

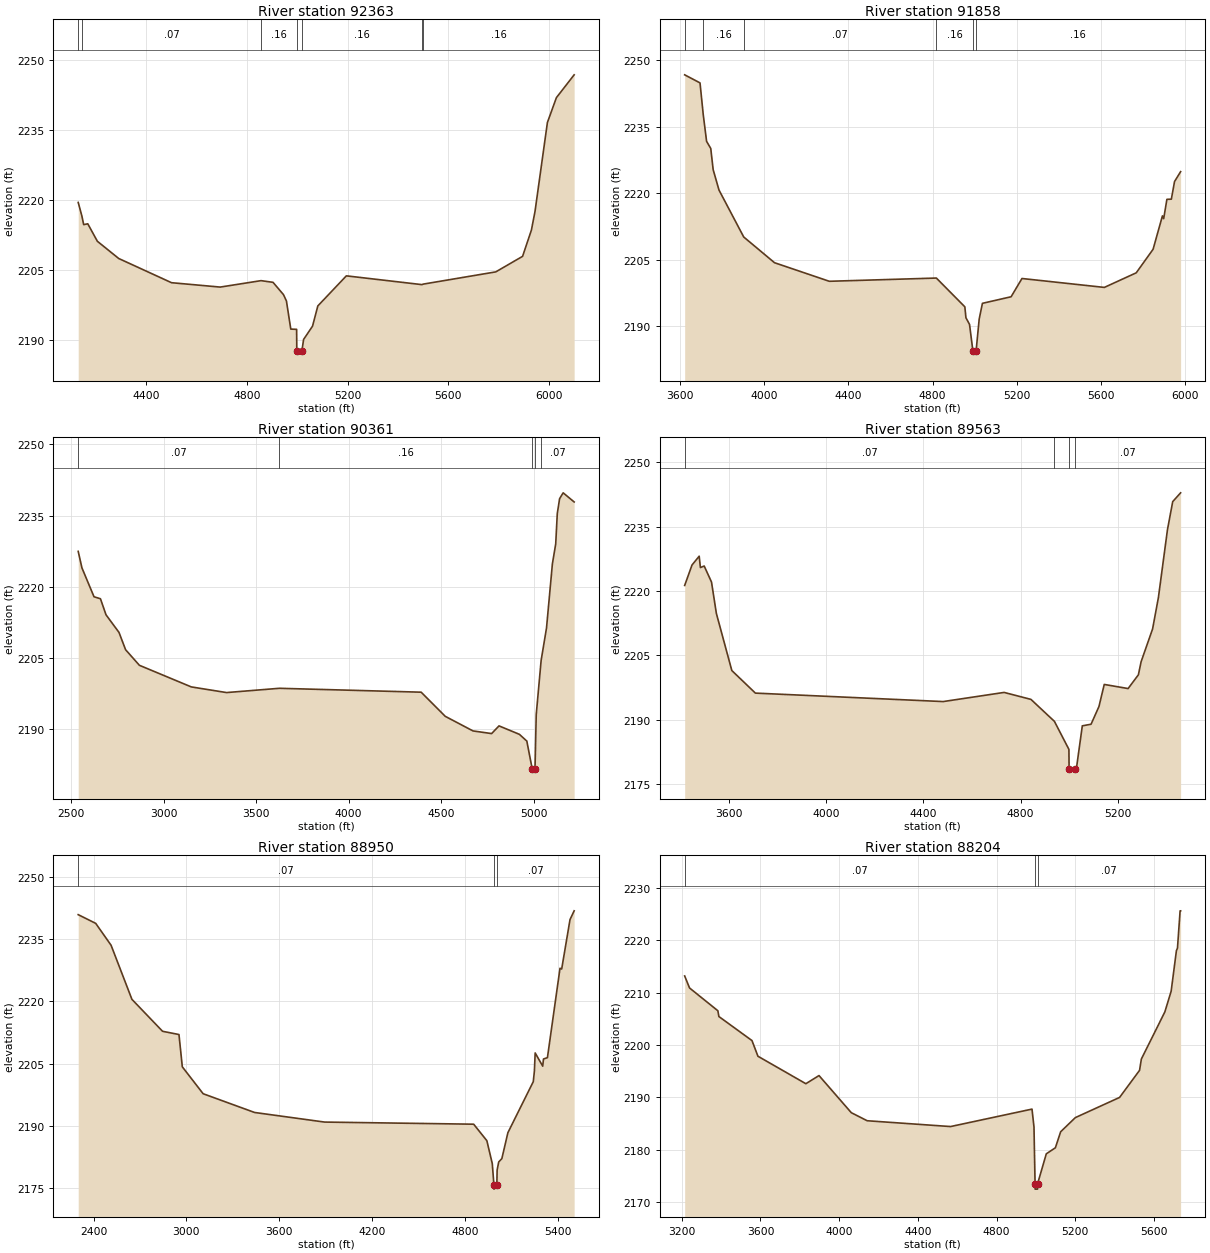
Type RM Length L Ch R = 1,92363,505,505,505
BEGIN DESCRIPTION:
Bitter Creek 82.0
END DESCRIPTION:
XS GIS Cut Line= 3
      1422055.00      6822138.01      1422399.80      6822937.53
      1423205.00      6823688.00
#Sta/Elev= 30
  4129.3 2219.50  4143.9 2216.59  4151.1 2214.74  4167.3 2214.92  4205.5 2211.17
  4290.3 2207.48  4500.2 2202.29  4693.8 2201.35  4856.1 2202.73  4903.7 2202.37
  4945.3 2199.73  4957.0 2198.37  4974.3 2192.34  4997.5 2192.29  4998.2 2187.69
  4998.6 2187.19  5018.5 2187.69  5025.2 2190.12  5060.8 2192.98  5081.8 2197.31
  5195.2 2203.76  5495.1 2201.88  5501.3 2201.99  5789.2 2204.61  5895.7 2207.94
  5930.9 2213.59  5945.1 2217.56  5994.4 2236.64  6030.1 2241.96  6100.7 2246.86
#Mann=7,-1,0
  4129.3    0.16       0  4143.9    0.07       0  4856.1    0.16       0
  4998.2    0.07       0  5018.5    0.16       0  5495.1    0.07       0
  5501.3    0.16       0
Bank Sta=4998.2,5018.5
Exp/Cntr=0.3,0.1

Type RM Length L Ch R = 1,91858,1497,1497,1497
BEGIN DESCRIPTION:
Bitter Creek 81.0
END DESCRIPTION:
XS GIS Cut Line= 3
      1421754.99      6821987.96      1422131.76      6823311.68
      1422954.99      6823838.00
#Sta/Elev= 30
  3623.7 2246.66  3696.5 2244.84  3711.9 2237.64  3727.7 2231.66  3747.5 2230.05
  3758.9 2225.27  3786.5 2220.68  3903.9 2210.09  4050.0 2204.29  4310.0 2200.10
  4818.0 2200.83  4953.2 2194.34  4958.4 2191.87  4975.4 2190.38  4991.4 2184.40
  4991.7 2183.90  5006.6 2184.40  5021.3 2191.59  5036.6 2195.13  5172.7 2196.61
  5224.3 2200.73  5615.1 2198.72  5766.5 2202.01  5846.5 2207.32  5890.8 2214.85
  5896.8 2214.22  5912.0 2218.58  5933.1 2218.62  5948.3 2222.60  5977.1 2224.82
#Mann=6,-1,0
  3623.7   0.063       0  3711.9    0.16       0  3903.9    0.07       0
  4818.0    0.16       0  4991.4    0.07       0  5006.6    0.16       0
Bank Sta=4991.4,5006.6
Exp/Cntr=0.3,0.1

Type RM Length L Ch R = 1,90361,798,798,798
BEGIN DESCRIPTION:
Bitter Creek 80.0
END DESCRIPTION:
XS GIS Cut Line= 3
      1421605.00      6822137.96      1421748.91      6824594.75
      1421817.58      6824802.60
#Sta/Elev= 30
  2539.0 2227.46  2559.1 2223.99  2624.4 2217.91  2659.2 2217.49  2689.3 2214.11
  2759.4 2210.41  2795.0 2206.77  2869.6 2203.49  3150.1 2198.94  3340.4 2197.75
  3626.2 2198.65  4392.2 2197.83  4522.4 2192.75  4672.2 2189.68  4772.9 2189.12
  4812.9 2190.74  4923.1 2188.96  4963.2 2187.54  4992.1 2181.72  4992.4 2181.22
  5007.4 2181.72  5014.0 2193.12  5040.5 2204.52  5069.6 2211.35  5101.3 2224.82
  5119.3 2229.03  5127.8 2235.43  5140.3 2238.55  5159.5 2239.78  5218.9 2237.86
#Mann=5,-1,0
  2539.0    0.07       0  3626.2    0.16       0  4992.1    0.07       0
  5007.4    0.16       0  5040.5    0.07       0
Bank Sta=4992.1,5007.4
Exp/Cntr=0.3,0.1

Type RM Length L Ch R = 1,89563,613,613,613
BEGIN DESCRIPTION:
Bitter Creek 79.0
END DESCRIPTION:
XS GIS Cut Line= 3
      1421055.00      6822987.95      1421178.36      6824564.73
      1421354.98      6824987.96
#Sta/Elev= 30
  3418.4 2221.29  3448.5 2226.04  3478.1 2228.10  3483.1 2225.46  3498.7 2225.81
  3528.8 2222.08  3548.8 2214.77  3612.4 2201.48  3709.3 2196.23  4481.7 2194.26
  4732.5 2196.39  4842.8 2194.77  4939.4 2189.66  4999.1 2183.13  4999.8 2178.57
  5000.3 2178.07  5025.3 2178.57  5030.4 2178.88  5054.2 2188.61  5090.2 2188.99
  5122.7 2193.11  5144.4 2198.25  5242.6 2197.29  5284.9 2200.49  5296.1 2203.54
  5343.3 2211.17  5367.2 2218.46  5404.5 2234.27  5426.1 2240.80  5458.6 2242.85
#Mann=4,-1,0
  3418.4    0.07       0  4939.4    0.16       0  4999.8    0.07       0
  5025.3    0.07       0
Bank Sta=4999.8,5025.3
Exp/Cntr=0.3,0.1

Type RM Length L Ch R = 1,88950,746,746,746
BEGIN DESCRIPTION:
Bitter Creek 78.0
END DESCRIPTION:
XS GIS Cut Line= 3
      1418804.99      6823138.00      1420806.34      6824948.56
      1421304.98      6825038.00
#Sta/Elev= 30
  2301.2 2240.84  2414.4 2238.74  2513.8 2233.47  2648.3 2220.47  2846.3 2212.78
  2952.4 2212.00  2974.1 2204.23  3108.6 2197.76  3441.1 2193.25  3893.9 2190.94
  4857.1 2190.43  4942.3 2186.47  4977.4 2180.97  4988.1 2175.81  4988.5 2174.81
  5006.9 2175.81  5008.8 2179.40  5019.0 2181.34  5039.3 2182.15  5078.3 2188.38
  5242.5 2200.67  5249.6 2203.17  5254.7 2207.57  5303.4 2204.39  5308.4 2206.11
  5333.9 2206.44  5415.2 2227.94  5426.0 2227.76  5479.8 2239.64  5506.6 2241.76
#Mann=3,-1,0
  2301.2    0.07       0  4988.1    0.07       0  5006.9    0.07       0
Bank Sta=4988.1,5006.9
Exp/Cntr=0.3,0.1

Type RM Length L Ch R = 1,88204,548,548,548
BEGIN DESCRIPTION:
Bitter Creek 77.0
END DESCRIPTION:
XS GIS Cut Line= 3
      1418636.08      6825269.55      1420404.50      6825512.96
      1421104.97      6825288.01
#Sta/Elev= 30
  3214.9 2213.18  3239.6 2210.89  3383.6 2206.54  3388.7 2205.44  3557.0 2200.85
  3587.3 2197.86  3830.8 2192.62  3897.7 2194.17  4061.7 2187.09  4142.5 2185.55
  4566.4 2184.44  4980.3 2187.77  4990.4 2184.36  4995.9 2173.50  4996.2 2172.50
  5008.2 2172.50  5008.5 2173.50  5053.0 2179.24  5099.1 2180.39  5126.0 2183.45
  5200.7 2186.15  5425.5 2190.00  5527.0 2195.17  5536.2 2197.33  5655.5 2206.31
  5687.6 2210.27  5714.4 2218.02  5719.7 2218.48  5733.1 2225.61  5735.7 2225.61
#Mann=3,-1,0
  3214.9    0.07       0  4995.9    0.07       0  5008.5    0.07       0
Bank Sta=4995.9,5008.5
Exp/Cntr=0.3,0.1

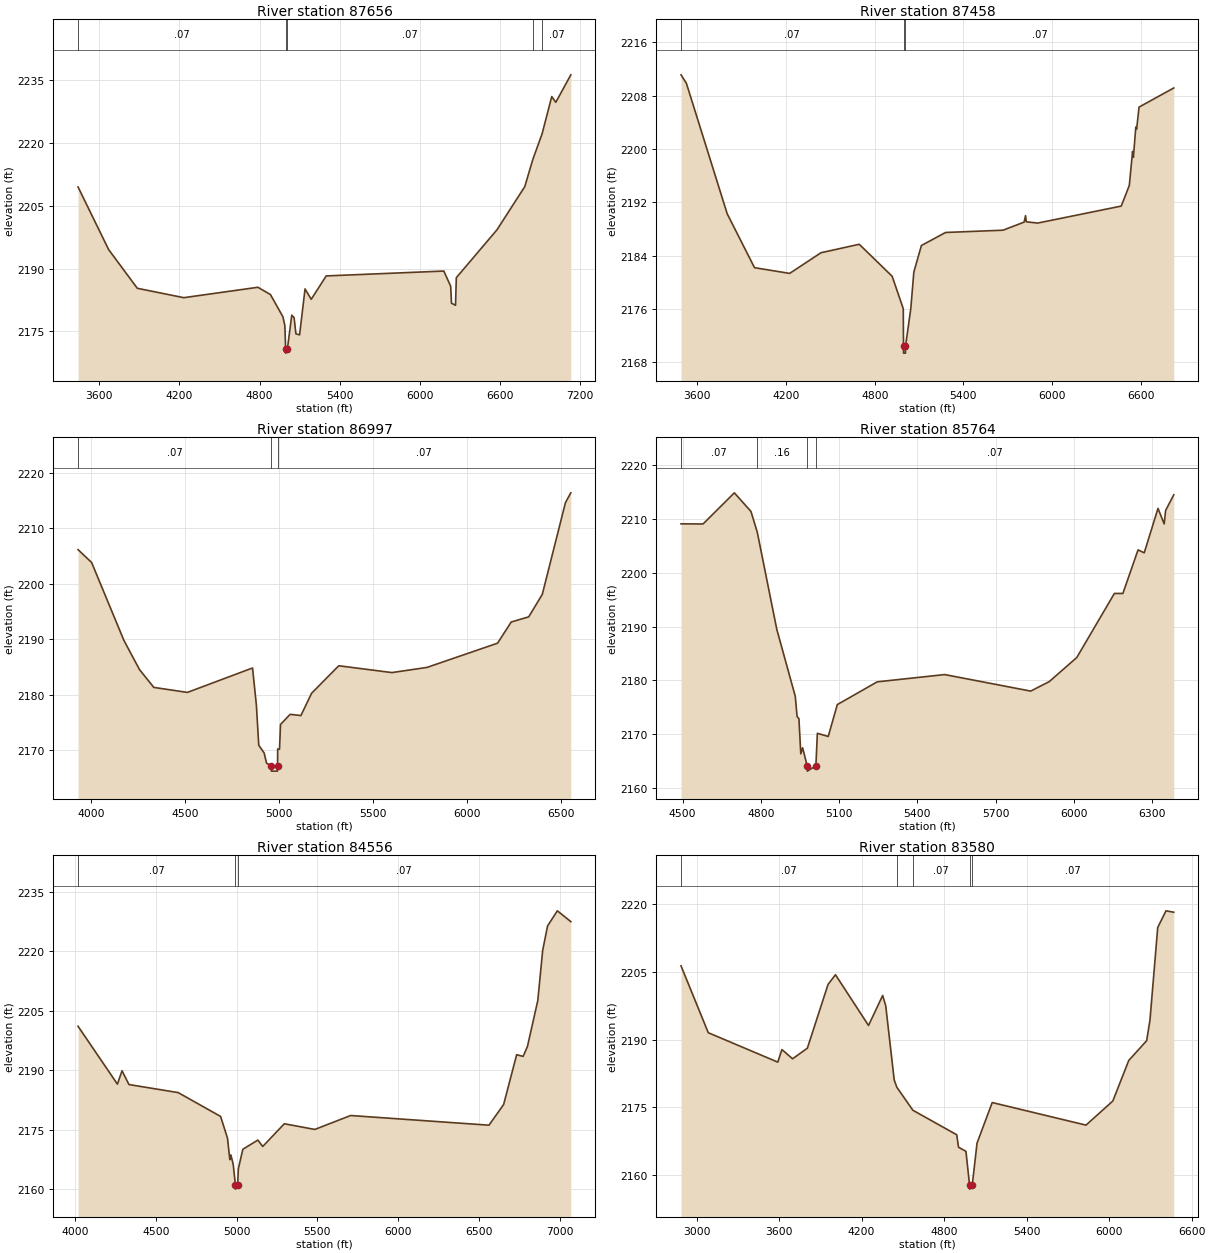
Type RM Length L Ch R = 1,87656,198,198,198
BEGIN DESCRIPTION:
Bitter Creek 4164
END DESCRIPTION:
XS GIS Cut Line= 4
      1418981.16      6825701.41      1420505.05      6826028.02
      1421227.80      6826211.39      1422385.79      6825452.41
#Sta/Elev= 30
  3441.5 2209.47  3670.4 2194.54  3885.2 2185.30  4232.9 2183.06  4787.7 2185.54
  4881.5 2183.81  4975.2 2178.50  4989.7 2176.37  4995.4 2170.83  4995.7 2169.83
  5008.7 2170.83  5041.2 2178.88  5058.8 2178.29  5072.2 2174.44  5099.8 2174.19
  5140.7 2185.15  5186.9 2182.67  5299.1 2188.25  6179.6 2189.41  6230.9 2185.80
  6236.9 2181.74  6267.1 2181.25  6273.1 2187.83  6577.6 2199.26  6785.5 2209.55
  6845.5 2216.01  6915.3 2222.17  6987.5 2231.04  7017.7 2229.67  7130.2 2236.23
#Mann=5,-1,0
  3441.5    0.07       0  4995.4    0.07       0  5008.7    0.07       0
  6845.5    0.16       0  6915.3    0.07       0
Bank Sta=4995.4,5008.7
Exp/Cntr=0.3,0.1

Type RM Length L Ch R = 1,87458,461,461,461
BEGIN DESCRIPTION:
Bitter Creek 4165
END DESCRIPTION:
XS GIS Cut Line= 4
      1418970.88      6825855.50      1420441.47      6826201.31
      1421366.69      6826398.02      1421778.47      6827173.92
#Sta/Elev= 30
  3489.3 2211.11  3525.8 2209.83  3801.7 2190.27  3986.6 2182.18  4224.5 2181.32
  4436.5 2184.42  4695.4 2185.69  4918.2 2180.89  4993.4 2176.03  4995.0 2170.36
  4995.3 2169.36  5008.1 2169.36  5008.4 2170.36  5044.5 2176.07  5065.0 2181.52
  5116.1 2185.50  5279.6 2187.46  5668.1 2187.80  5811.3 2189.01  5821.0 2189.98
  5826.1 2189.06  5903.3 2188.87  6468.6 2191.42  6523.2 2194.51  6545.2 2199.62
  6550.9 2198.73  6567.2 2203.28  6572.9 2202.98  6589.2 2206.27  6824.3 2209.14
#Mann=3,-1,0
  3489.3    0.07       0  4995.0    0.07       0  5008.4    0.07       0
Bank Sta=4995,5008.4
Exp/Cntr=0.3,0.1

Type RM Length L Ch R = 1,86997,1233,1233,1233
BEGIN DESCRIPTION:
Bitter Creek 76.4
END DESCRIPTION:
XS GIS Cut Line= 3
      1419023.53      6826024.91      1420061.02      6826279.19
      1421354.96      6827137.98
#Sta/Elev= 30
  3931.8 2206.13  4004.0 2203.81  4175.6 2189.79  4258.7 2184.52  4334.9 2181.31
  4513.5 2180.41  4860.0 2184.81  4880.5 2178.10  4893.0 2170.90  4921.7 2169.50
  4934.6 2167.65  4959.6 2167.23  4960.4 2166.23  4992.3 2166.23  4993.0 2167.23
  4993.8 2170.22  5003.4 2170.16  5008.8 2174.64  5060.0 2176.46  5117.1 2176.24
  5174.2 2180.26  5318.6 2185.21  5601.3 2183.98  5787.7 2184.91  6163.6 2189.28
  6235.8 2193.09  6329.0 2194.02  6401.2 2198.06  6524.5 2214.60  6553.0 2216.36
#Mann=3,-1,0
  3931.8    0.07       0  4959.6    0.07       0  4993.0    0.07       0
Bank Sta=4959.6,4993
Exp/Cntr=0.3,0.1

Type RM Length L Ch R = 1,85764,1208,1208,1208
BEGIN DESCRIPTION:
Bitter Creek 76.3
END DESCRIPTION:
XS GIS Cut Line= 3
      1418796.07      6826477.82      1419151.33      6826838.00
      1420424.64      6827377.01
#Sta/Elev= 30
  4494.1 2209.10  4578.4 2209.07  4698.5 2214.86  4762.1 2211.40  4786.3 2207.56
  4861.1 2189.51  4931.9 2177.06  4939.0 2173.30  4946.0 2172.88  4953.1 2166.36
  4960.1 2167.49  4977.5 2164.15  4978.2 2163.15  5011.0 2164.15  5016.6 2170.18
  5058.3 2169.59  5093.0 2175.51  5246.0 2179.74  5504.6 2181.09  5834.2 2178.02
  5905.3 2179.78  6010.9 2184.26  6155.0 2196.16  6187.5 2196.16  6245.8 2204.26
  6269.4 2203.71  6322.2 2211.97  6345.9 2209.09  6351.4 2211.59  6382.7 2214.50
#Mann=4,-1,0
  4494.1    0.07       0  4786.3    0.16       0  4977.5    0.07       0
  5011.0    0.07       0
Bank Sta=4977.5,5011
Exp/Cntr=0.3,0.1

Type RM Length L Ch R = 1,84556,976,976,976
BEGIN DESCRIPTION:
Bitter Creek 76.2
END DESCRIPTION:
XS GIS Cut Line= 3
      1417404.12      6826625.63      1418154.52      6827258.13
      1420207.85      6827504.85
#Sta/Elev= 30
  4018.6 2201.10  4262.2 2186.50  4290.8 2189.87  4333.6 2186.40  4638.1 2184.37
  4900.7 2178.36  4943.6 2172.87  4957.9 2167.45  4964.5 2168.65  4978.8 2166.26
  4992.7 2161.03  4993.0 2160.03  5006.1 2161.03  5010.6 2165.15  5038.3 2170.08
  5131.4 2172.39  5161.6 2170.79  5295.0 2176.51  5483.9 2175.08  5705.5 2178.59
  6561.6 2176.15  6652.3 2181.36  6732.9 2193.92  6773.1 2193.50  6799.7 2196.00
  6863.8 2207.59  6894.0 2220.24  6924.2 2226.39  6984.7 2230.20  7068.1 2227.48
#Mann=3,-1,0
  4018.6    0.07       0  4992.7    0.07       0  5006.1    0.07       0
Bank Sta=4992.7,5006.1
Exp/Cntr=0.3,0.1

Type RM Length L Ch R = 1,83580,2185,2185,2185
BEGIN DESCRIPTION:
Bitter Creek 76.1
END DESCRIPTION:
XS GIS Cut Line= 3
      1416430.74      6827072.13      1418395.47      6827849.14
      1419861.63      6827740.10
#Sta/Elev= 30
  2887.2 2206.28  3085.3 2191.51  3590.8 2185.01  3620.7 2187.78  3698.3 2185.75
  3805.8 2188.09  3956.4 2202.19  4010.2 2204.32  4250.6 2193.11  4353.4 2199.74
  4375.8 2197.43  4437.2 2181.09  4456.6 2179.45  4573.1 2174.38  4892.0 2168.96
  4904.9 2166.21  4959.0 2165.30  4984.9 2157.95  4985.4 2156.95  5005.1 2157.95
  5039.6 2167.12  5149.9 2176.08  5831.8 2171.09  6027.0 2176.42  6142.7 2185.38
  6273.0 2189.75  6297.2 2194.36  6353.3 2214.75  6413.4 2218.44  6470.2 2218.13
#Mann=5,-1,0
  2887.2    0.07       0  4456.6    0.16       0  4573.1    0.07       0
  4984.9    0.07       0  5005.1    0.07       0
Bank Sta=4984.9,5005.1
Exp/Cntr=0.3,0.1

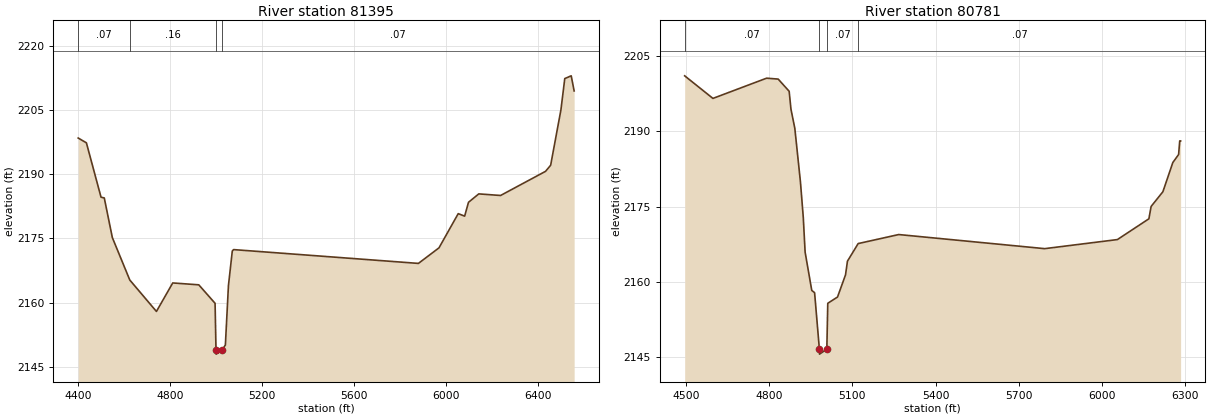
Type RM Length L Ch R = 1,81395,614,614,614
BEGIN DESCRIPTION:
Bitter Creek 76.0
END DESCRIPTION:
XS GIS Cut Line= 3
      1417755.02      6829087.98      1418149.65      6828635.22
      1419541.13      6827937.08
#Sta/Elev= 30
  4399.4 2198.42  4435.0 2197.31  4498.6 2184.63  4512.8 2184.44  4547.9 2175.19
  4623.8 2165.29  4739.7 2157.96  4810.6 2164.61  4923.9 2164.17  4994.8 2159.86
  4998.8 2149.00  4999.4 2148.00  5025.7 2149.00  5039.6 2150.13  5052.9 2163.99
  5069.7 2172.05  5075.3 2172.39  5879.4 2169.17  5968.8 2172.80  6052.5 2180.78
  6080.5 2180.20  6097.2 2183.43  6141.9 2185.39  6236.8 2185.02  6432.3 2190.65
  6454.6 2192.08  6499.3 2205.01  6516.0 2212.30  6544.0 2212.94  6556.8 2209.42
#Mann=4,-1,0
  4399.4    0.07       0  4623.8    0.16       0  4998.8    0.07       0
  5025.7    0.07       0
Bank Sta=4998.8,5025.7
Exp/Cntr=0.3,0.1

Type RM Length L Ch R = 1,80781,747,747,747
BEGIN DESCRIPTION:
Bitter Creek 75.0
END DESCRIPTION:
XS GIS Cut Line= 3
      1417555.00      6829288.00      1418050.91      6829189.50
      1419055.03      6828387.97
#Sta/Elev= 30
  4494.4 2201.05  4596.4 2196.55  4790.1 2200.58  4832.0 2200.40  4871.6 2197.97
  4878.1 2194.40  4892.0 2190.60  4912.4 2179.88  4922.6 2172.82  4929.2 2165.92
  4953.2 2158.28  4963.4 2157.84  4980.7 2146.59  4981.3 2145.59  5007.6 2146.59
  5011.0 2155.72  5046.2 2156.97  5075.1 2161.39  5082.0 2164.11  5120.7 2167.62
  5267.2 2169.42  5794.0 2166.61  6056.6 2168.42  6170.3 2172.56  6178.3 2175.02
  6220.8 2177.95  6256.7 2183.77  6277.6 2185.37  6281.6 2188.08  6284.8 2188.08
#Mann=4,-1,0
  4494.4    0.07       0  4980.7    0.07       0  5007.6    0.07       0
  5120.7    0.07       0
Bank Sta=4980.7,5007.6
Exp/Cntr=0.3,0.1