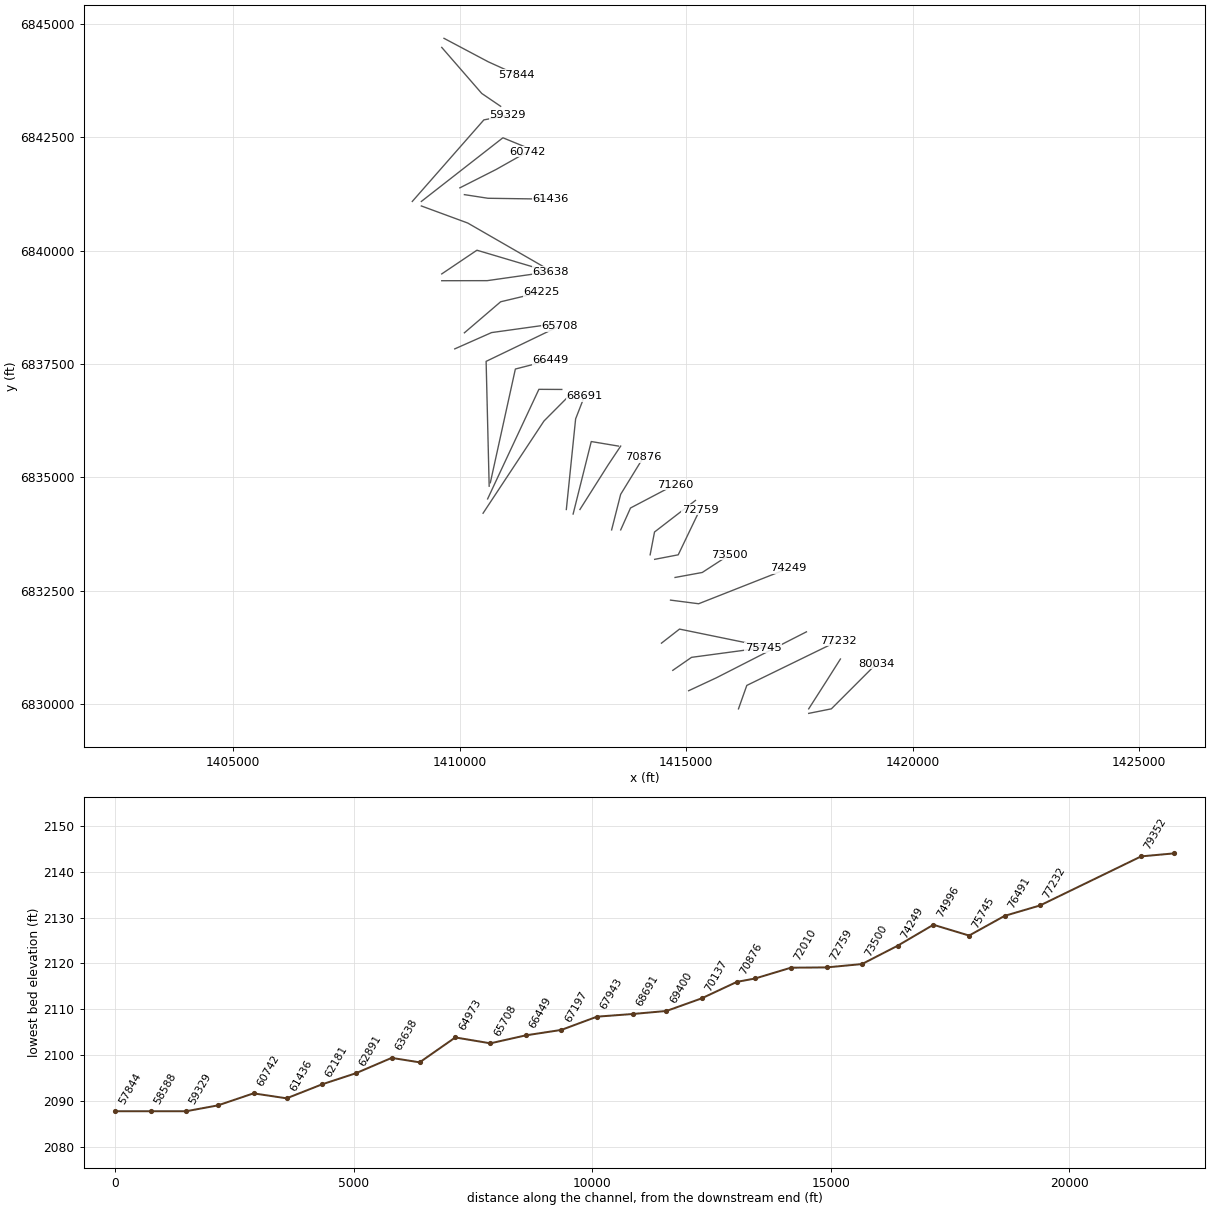
HEC-RAS study Bitter Creek.prj: Bitter Creek Base Level Engineering

--- Bitter Creek.g01 (geometry) --- (continued)

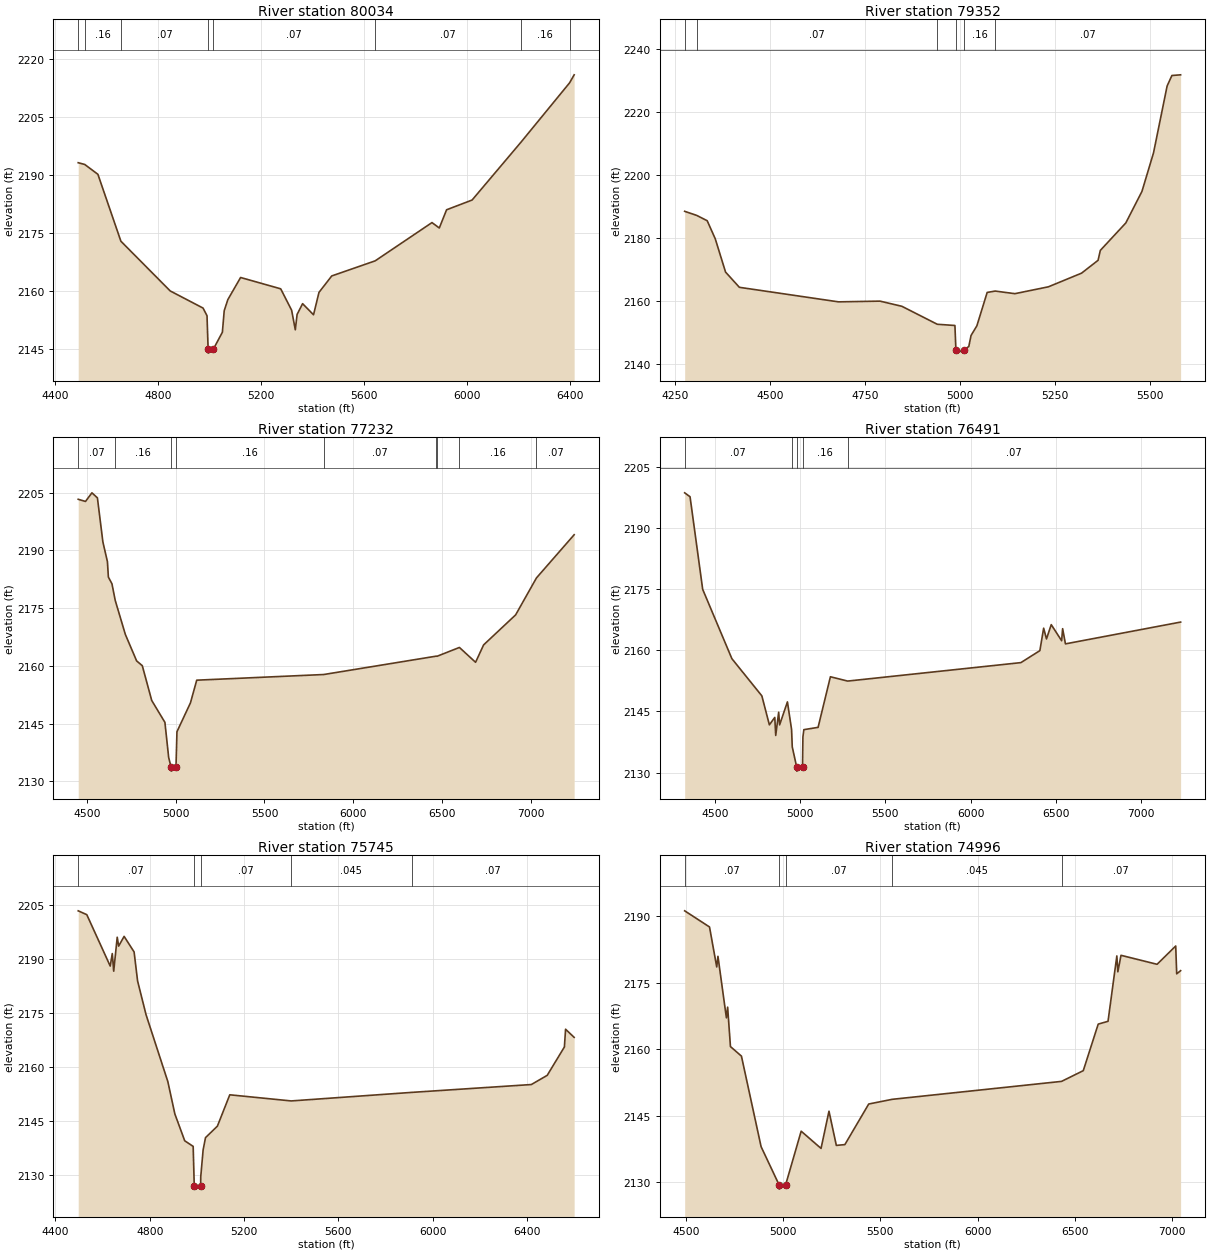
Type RM Length L Ch R = 1,80034,682,682,682
BEGIN DESCRIPTION:
Bitter Creek 74.0
END DESCRIPTION:
XS GIS Cut Line= 3
      1417705.04      6829788.01      1418204.93      6829888.03
      1419204.97      6830887.97
#Sta/Elev= 30
  4490.2 2193.19  4515.5 2192.74  4566.6 2190.19  4655.8 2172.89  4847.1 2160.03
  4974.5 2155.60  4989.9 2153.62  4994.2 2144.95  4994.6 2143.95  5014.3 2144.95
  5049.5 2149.36  5056.6 2154.91  5070.7 2157.79  5120.2 2163.51  5275.8 2160.58
  5318.2 2155.04  5332.4 2149.99  5339.4 2153.96  5360.7 2156.74  5403.1 2153.87
  5424.3 2159.66  5473.8 2163.91  5642.2 2167.81  5862.7 2177.71  5891.0 2176.31
  5919.3 2181.02  6018.3 2183.54  6207.3 2198.45  6396.4 2213.84  6414.2 2215.92
#Mann=8,-1,0
  4490.2    0.07       0  4515.5    0.16       0  4655.8    0.07       0
  4994.2    0.07       0  5014.3    0.07       0  5642.2    0.07       0
  6207.3    0.16       0  6396.4    0.07       0
Bank Sta=4994.2,5014.3
Exp/Cntr=0.3,0.1

Type RM Length L Ch R = 1,79352,2120,2120,2120
BEGIN DESCRIPTION:
Bitter Creek 73.0
END DESCRIPTION:
XS GIS Cut Line= 3
      1417704.98      6829887.97      1418095.01      6830498.05
      1418405.01      6830988.01
#Sta/Elev= 30
  4275.9 2188.35  4307.5 2187.06  4335.1 2185.37  4356.3 2179.62  4383.4 2169.05
  4419.7 2164.21  4680.3 2159.59  4789.4 2159.82  4846.9 2158.18  4940.0 2152.47
  4986.4 2152.08  4989.0 2144.30  4989.4 2143.30  5009.2 2144.30  5022.9 2145.40
  5028.8 2148.91  5044.1 2151.97  5071.2 2162.58  5092.3 2163.02  5144.1 2162.19
  5232.2 2164.37  5319.4 2168.71  5362.8 2172.79  5368.7 2175.94  5435.7 2184.66
  5478.1 2194.67  5508.6 2206.95  5544.3 2228.17  5556.9 2231.50  5579.8 2231.72
#Mann=6,-1,0
  4275.9    0.16       0  4307.5    0.07       0  4940.0    0.16       0
  4989.0    0.07       0  5009.2    0.16       0  5092.3    0.07       0
Bank Sta=4989,5009.2
Exp/Cntr=0.3,0.1

Type RM Length L Ch R = 1,77232,741,741,741
BEGIN DESCRIPTION:
Bitter Creek 72.0
END DESCRIPTION:
XS GIS Cut Line= 3
      1416155.00      6829887.99      1416338.41      6830405.02
      1418354.99      6831388.00
#Sta/Elev= 30
  4451.4 2203.31  4492.4 2202.75  4528.6 2204.99  4559.5 2203.68  4590.3 2192.22
  4615.9 2187.09  4621.2 2183.09  4641.5 2181.32  4659.7 2177.03  4716.7 2168.18
  4780.3 2161.28  4812.2 2160.04  4865.2 2151.00  4939.5 2145.30  4960.7 2136.16
  4974.5 2133.62  4975.1 2132.62  5001.8 2133.62  5007.3 2142.87  5083.2 2150.36
  5118.6 2156.27  5833.3 2157.74  6467.2 2162.52  6471.8 2162.49  6597.5 2164.78
  6688.5 2160.92  6733.6 2165.44  6913.9 2173.25  7031.4 2182.87  7243.4 2194.09
#Mann=9,-1,0
  4451.4    0.07       0  4659.7    0.16       0  4974.5    0.07       0
  5001.8    0.16       0  5833.3    0.07       0  6467.2    0.16       0
  6471.8    0.07       0  6597.5    0.16       0  7031.4    0.07       0
Bank Sta=4974.5,5001.8
Exp/Cntr=0.3,0.1

Type RM Length L Ch R = 1,76491,746,746,746
BEGIN DESCRIPTION:
Bitter Creek 71.0
END DESCRIPTION:
XS GIS Cut Line= 3
      1415055.05      6830288.02      1415668.04      6830573.95
      1417655.03      6831588.02
#Sta/Elev= 30
  4323.6 2198.66  4355.1 2197.70  4429.2 2174.97  4600.3 2157.96  4776.0 2148.83
  4820.1 2141.72  4851.7 2143.54  4857.3 2139.12  4874.6 2144.81  4880.1 2141.71
  4925.9 2147.35  4950.3 2140.57  4954.2 2136.32  4980.2 2131.36  4980.9 2130.36
  5014.3 2131.36  5016.7 2138.77  5022.3 2140.54  5105.6 2141.10  5177.9 2153.52
  5279.1 2152.46  6294.6 2156.99  6405.7 2159.93  6427.9 2165.44  6444.5 2162.80
  6472.4 2166.31  6533.4 2162.36  6539.1 2165.32  6555.7 2161.59  7230.8 2166.94
#Mann=5,-1,0
  4323.6    0.07       0  4950.3    0.16       0  4980.2    0.07       0
  5014.3    0.16       0  5279.1    0.07       0
Bank Sta=4980.2,5014.3
Exp/Cntr=0.3,0.1

Type RM Length L Ch R = 1,75745,749,749,749
BEGIN DESCRIPTION:
Bitter Creek 70.0
END DESCRIPTION:
XS GIS Cut Line= 3
      1414705.02      6830738.02      1415118.63      6831024.79
      1416704.97      6831238.00
#Sta/Elev= 30
  4496.7 2203.29  4533.2 2202.22  4632.5 2187.96  4641.2 2191.43  4647.3 2186.55
  4662.2 2195.97  4668.3 2193.50  4691.4 2196.20  4733.8 2191.88  4748.6 2183.83
  4784.4 2174.49  4877.0 2155.89  4906.7 2146.93  4948.6 2139.48  4984.4 2137.93
  4988.9 2127.07  4989.5 2126.07  5016.2 2127.07  5016.5 2129.48  5026.6 2136.95
  5036.7 2140.35  5087.1 2143.54  5139.7 2152.24  5400.3 2150.54  5911.1 2152.91
  6419.0 2155.09  6486.3 2157.64  6559.2 2165.51  6564.2 2170.44  6600.6 2168.18
#Mann=5,-1,0
  4496.7    0.07       0  4988.9    0.07       0  5016.2    0.07       0
  5400.3   0.045       0  5911.1    0.07       0
Bank Sta=4988.9,5016.2
Exp/Cntr=0.3,0.1

Type RM Length L Ch R = 1,74996,747,747,747
BEGIN DESCRIPTION:
Bitter Creek 69.0
END DESCRIPTION:
XS GIS Cut Line= 3
      1414454.98      6831337.99      1414853.50      6831648.49
      1416855.04      6831237.99
#Sta/Elev= 30
  4494.8 2191.24  4622.4 2187.60  4659.5 2178.57  4665.8 2180.97  4709.2 2167.09
  4715.6 2169.50  4730.0 2160.60  4786.4 2158.45  4887.5 2138.00  4979.6 2129.42
  4980.4 2128.42  5013.8 2129.42  5093.4 2141.50  5195.5 2137.61  5236.3 2146.01
  5274.1 2138.29  5318.0 2138.47  5440.5 2147.63  5561.2 2148.69  6431.4 2152.74
  6543.0 2155.16  6619.8 2165.67  6670.2 2166.30  6715.5 2181.06  6720.6 2177.47
  6736.9 2181.20  6922.2 2179.17  7018.0 2183.30  7023.1 2177.02  7043.2 2177.73
#Mann=5,-1,0
  4494.8    0.07       0  4979.6    0.07       0  5013.8    0.07       0
  5561.2   0.045       0  6431.4    0.07       0
Bank Sta=4979.6,5013.8
Exp/Cntr=0.3,0.1

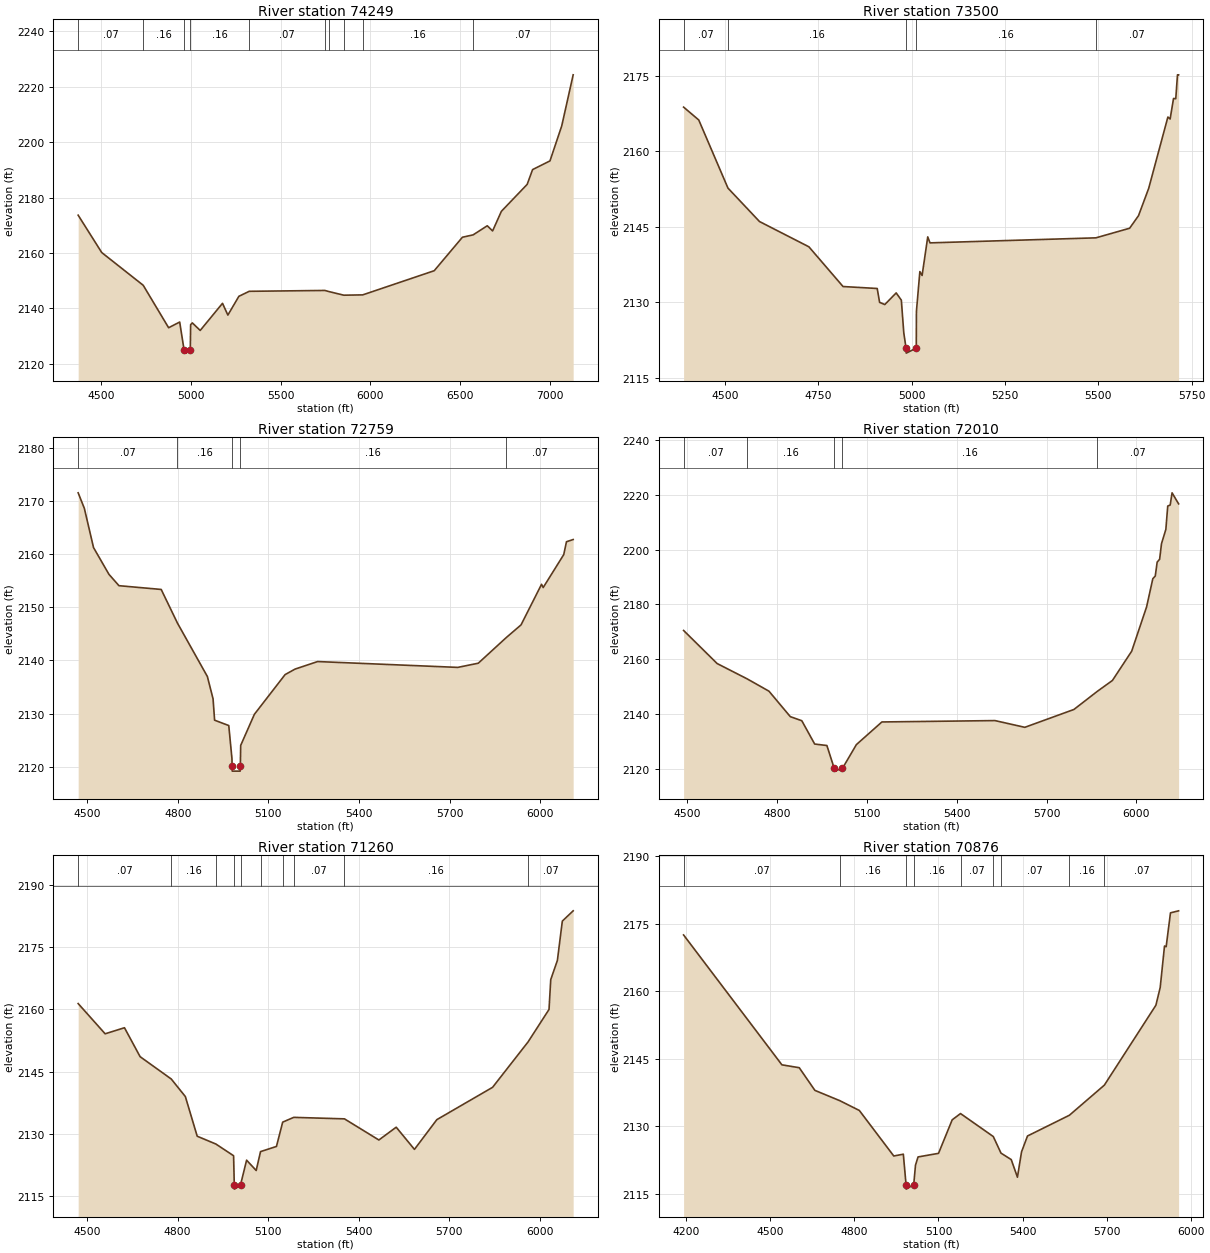
Type RM Length L Ch R = 1,74249,749,749,749
BEGIN DESCRIPTION:
Bitter Creek 68.0
END DESCRIPTION:
XS GIS Cut Line= 3
      1414654.98      6832288.00      1415275.42      6832207.83
      1417255.03      6832988.01
#Sta/Elev= 30
  4374.4 2173.65  4505.5 2160.17  4736.2 2148.36  4877.6 2133.03  4939.1 2135.09
  4963.9 2124.87  4964.7 2123.87  4998.1 2124.87  5000.0 2134.14  5009.5 2134.78
  5053.3 2132.06  5177.3 2141.85  5207.1 2137.60  5268.3 2144.37  5325.9 2146.18
  5746.8 2146.49  5767.8 2146.11  5852.0 2144.78  5957.2 2144.89  6354.9 2153.61
  6511.9 2165.70  6571.4 2166.55  6650.0 2169.83  6679.7 2167.97  6728.5 2175.05
  6871.9 2184.77  6902.1 2190.11  6998.8 2193.24  7064.1 2205.85  7127.8 2224.31
#Mann=10,-1,0
  4374.4    0.07       0  4736.2    0.16       0  4963.9    0.07       0
  4998.1    0.16       0  5325.9    0.07       0  5746.8   0.045       0
  5767.8    0.16       0  5852.0   0.045       0  5957.2    0.16       0
  6571.4    0.07       0
Bank Sta=4963.9,4998.1
Exp/Cntr=0.3,0.1

Type RM Length L Ch R = 1,73500,741,741,741
BEGIN DESCRIPTION:
Bitter Creek 67.0
END DESCRIPTION:
XS GIS Cut Line= 3
      1414755.03      6832788.01      1415355.51      6832898.21
      1415955.02      6833288.01
#Sta/Elev= 30
  4389.5 2168.78  4430.1 2166.22  4508.3 2152.68  4592.8 2146.03  4725.0 2141.01
  4816.5 2133.11  4908.0 2132.72  4914.4 2129.96  4928.3 2129.53  4958.8 2131.84
  4972.6 2130.40  4979.2 2123.88  4985.2 2120.87  4985.8 2119.87  5012.6 2120.87
  5013.0 2128.17  5022.2 2136.08  5028.2 2135.31  5043.3 2142.98  5049.3 2141.79
  5493.6 2142.79  5583.9 2144.70  5607.7 2147.19  5635.0 2152.63  5686.4 2166.81
  5692.4 2166.42  5701.5 2170.50  5707.5 2170.45  5712.1 2175.20  5715.1 2175.20
#Mann=5,-1,0
  4389.5    0.07       0  4508.3    0.16       0  4985.2    0.07       0
  5012.6    0.16       0  5493.6    0.07       0
Bank Sta=4985.2,5012.6
Exp/Cntr=0.3,0.1

Type RM Length L Ch R = 1,72759,749,749,749
BEGIN DESCRIPTION:
Bitter Creek 66.0
END DESCRIPTION:
XS GIS Cut Line= 3
      1414305.00      6833188.00      1414824.98      6833287.96
      1415305.01      6834288.02
#Sta/Elev= 30
  4470.5 2171.59  4490.9 2168.68  4521.4 2161.27  4572.3 2156.24  4605.5 2154.09
  4745.4 2153.38  4799.1 2147.05  4898.2 2136.98  4917.1 2132.77  4922.2 2128.74
  4969.1 2127.73  4979.7 2121.48  4980.0 2120.14  4980.6 2119.14  5006.8 2119.14
  5007.4 2120.14  5008.6 2123.99  5053.9 2129.85  5155.6 2137.33  5188.6 2138.37
  5263.3 2139.79  5727.3 2138.69  5795.2 2139.48  5887.4 2144.29  5936.7 2146.70
  6004.6 2154.35  6010.1 2153.74  6078.1 2159.95  6087.1 2162.37  6109.3 2162.79
#Mann=5,-1,0
  4470.5    0.07       0  4799.1    0.16       0  4980.0    0.07       0
  5007.4    0.16       0  5887.4    0.07       0
Bank Sta=4980,5007.4
Exp/Cntr=0.3,0.1

Type RM Length L Ch R = 1,72010,750,750,750
BEGIN DESCRIPTION:
Bitter Creek 65.0
END DESCRIPTION:
XS GIS Cut Line= 3
      1414205.00      6833288.02      1414301.66      6833791.32
      1415205.02      6834488.01
#Sta/Elev= 30
  4487.5 2170.49  4599.5 2158.40  4699.9 2152.79  4772.6 2148.30  4843.9 2138.99
  4882.3 2137.50  4925.3 2128.98  4966.1 2128.44  4990.6 2120.08  4991.2 2119.08
  5018.0 2120.08  5064.6 2128.77  5149.8 2137.05  5527.5 2137.55  5627.2 2135.09
  5791.1 2141.61  5869.5 2148.25  5919.8 2152.22  5984.1 2162.91  6033.9 2179.11
  6054.7 2189.41  6062.9 2190.40  6069.2 2195.47  6077.4 2196.51  6083.7 2202.23
  6098.2 2207.41  6104.5 2215.95  6112.7 2216.33  6119.0 2220.79  6140.8 2216.76
#Mann=5,-1,0
  4487.5    0.07       0  4699.9    0.16       0  4990.6    0.07       0
  5018.0    0.16       0  5869.5    0.07       0
Bank Sta=4990.6,5018
Exp/Cntr=0.3,0.1

Type RM Length L Ch R = 1,71260,384,384,384
BEGIN DESCRIPTION:
Bitter Creek 64.0
END DESCRIPTION:
XS GIS Cut Line= 3
      1413554.99      6833837.97      1413771.66      6834321.33
      1414754.99      6834838.00
#Sta/Elev= 30
  4470.3 2161.41  4559.7 2154.13  4623.8 2155.59  4675.6 2148.62  4778.9 2143.24
  4825.6 2139.01  4864.8 2129.47  4926.7 2127.59  4985.4 2124.77  4987.7 2117.73
  4988.2 2116.73  5008.3 2117.73  5028.5 2123.70  5060.3 2121.22  5074.7 2125.76
  5127.5 2127.01  5148.1 2132.86  5184.8 2134.01  5352.8 2133.65  5466.9 2128.56
  5524.3 2131.64  5584.8 2126.30  5659.0 2133.46  5843.7 2141.24  5961.5 2152.19
  6030.8 2160.00  6036.5 2167.18  6058.5 2171.80  6074.9 2181.27  6110.8 2183.74
#Mann=10,-1,0
  4470.3    0.07       0  4778.9    0.16       0  4926.7    0.07       0
  4987.7    0.07       0  5008.3    0.07       0  5074.7    0.07       0
  5148.1    0.16       0  5184.8    0.07       0  5352.8    0.16       0
  5961.5    0.07       0
Bank Sta=4987.7,5008.3
Exp/Cntr=0.3,0.1

Type RM Length L Ch R = 1,70876,739,739,739
BEGIN DESCRIPTION:
Bitter Creek 63.0
END DESCRIPTION:
XS GIS Cut Line= 3
      1413355.00      6833838.01      1413554.12      6834622.64
      1414054.99      6835437.98
#Sta/Elev= 30
  4190.5 2172.53  4541.3 2143.64  4603.2 2143.00  4659.0 2137.96  4748.5 2135.65
  4817.6 2133.49  4940.5 2123.36  4974.6 2123.76  4984.3 2116.99  4984.9 2115.99
  5011.7 2116.99  5018.0 2121.32  5027.1 2123.15  5100.2 2123.95  5149.0 2131.41
  5178.7 2132.80  5295.6 2127.69  5323.1 2124.00  5359.7 2122.56  5381.8 2118.64
  5396.4 2124.28  5417.7 2127.81  5567.3 2132.43  5691.9 2139.12  5875.8 2156.89
  5891.2 2160.83  5906.6 2170.07  5912.5 2169.92  5927.9 2177.45  5956.9 2177.90
#Mann=9,-1,0
  4190.5    0.07       0  4748.5    0.16       0  4984.3    0.07       0
  5011.7    0.16       0  5178.7    0.07       0  5295.6    0.16       0
  5323.1    0.07       0  5567.3    0.16       0  5691.9    0.07       0
Bank Sta=4984.3,5011.7
Exp/Cntr=0.3,0.1

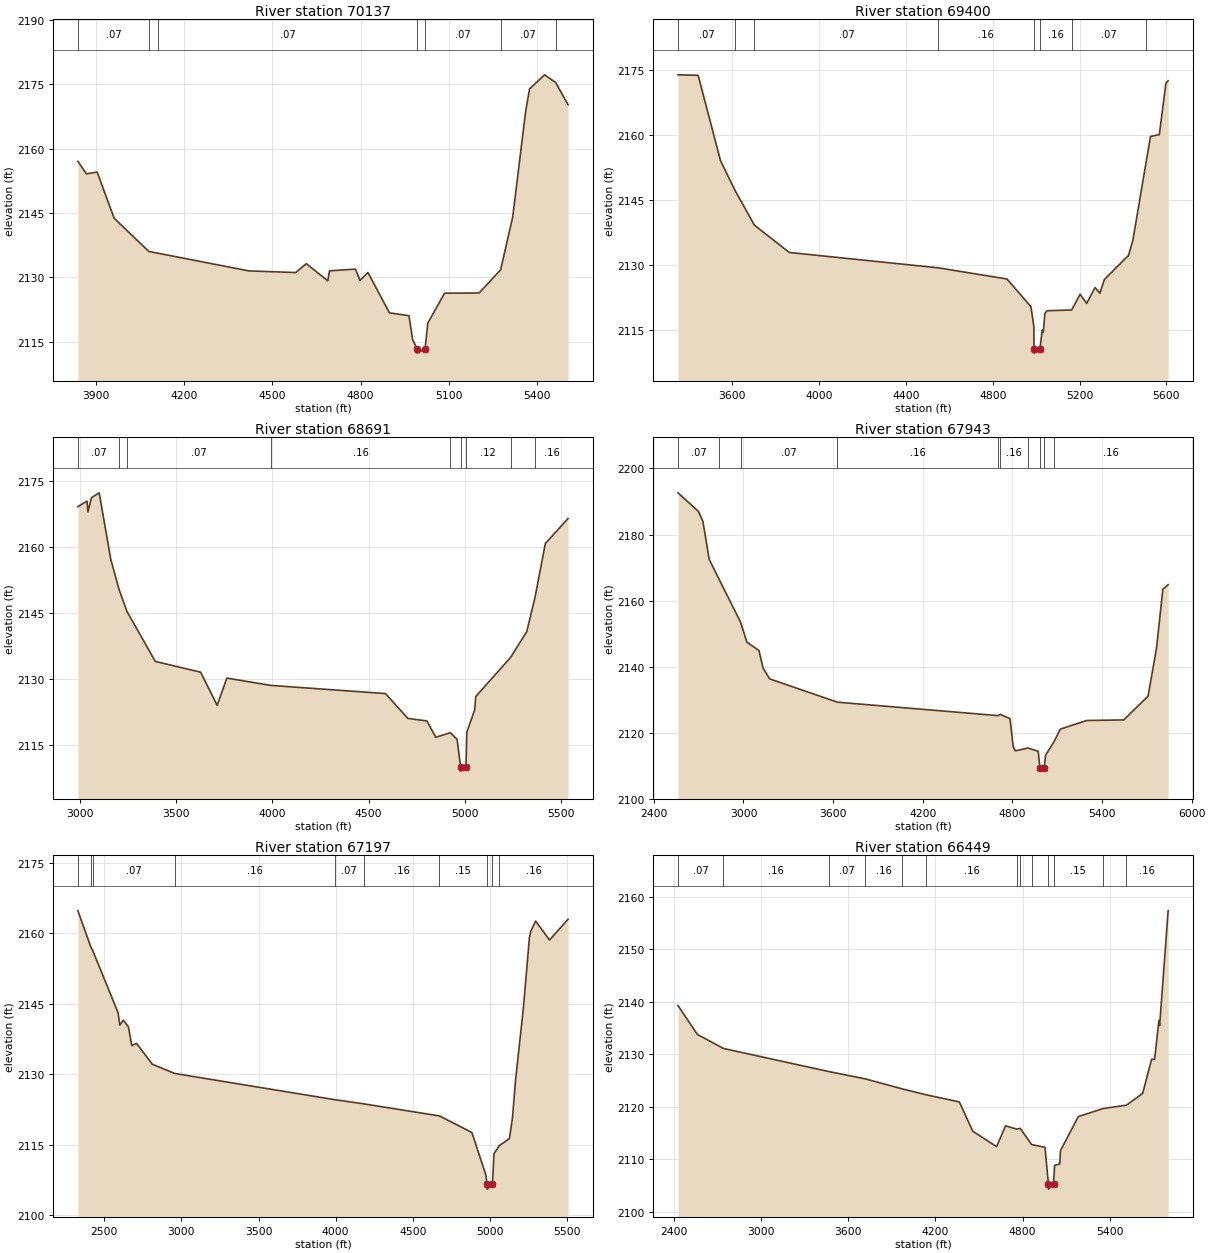
Type RM Length L Ch R = 1,70137,737,737,737
BEGIN DESCRIPTION:
Bitter Creek 62.0
END DESCRIPTION:
XS GIS Cut Line= 3
      1412654.98      6834287.96      1413275.32      6835268.27
      1413555.01      6835688.02
#Sta/Elev= 30
  3839.9 2157.02  3868.8 2154.11  3905.2 2154.54  3962.9 2143.80  4080.5 2136.07
  4111.8 2135.65  4419.8 2131.54  4579.1 2131.15  4615.6 2133.21  4688.5 2129.23
  4694.4 2131.55  4782.5 2131.95  4797.8 2129.32  4824.9 2131.16  4897.8 2121.78
  4964.2 2121.10  4976.6 2115.55  4991.5 2113.40  4992.1 2112.40  5019.0 2113.40
  5028.1 2119.39  5085.2 2126.35  5202.4 2126.39  5275.4 2131.79  5316.6 2144.13
  5360.2 2168.58  5373.7 2173.89  5424.7 2177.16  5462.3 2175.38  5504.4 2170.21
#Mann=7,-1,0
  3839.9    0.07       0  4080.5    0.16       0  4111.8    0.07       0
  4991.5    0.07       0  5019.0    0.07       0  5275.4    0.07       0
  5462.3    0.16       0
Bank Sta=4991.5,5019
Exp/Cntr=0.3,0.1

Type RM Length L Ch R = 1,69400,709,709,709
BEGIN DESCRIPTION:
Bitter Creek 61.0
END DESCRIPTION:
XS GIS Cut Line= 3
      1412504.99      6834187.95      1412905.33      6835788.13
      1413505.03      6835688.00
#Sta/Elev= 30
  3350.5 2173.89  3443.3 2173.78  3546.4 2154.07  3613.7 2147.15  3702.6 2139.19
  3863.2 2132.89  4550.1 2129.34  4865.9 2126.77  4976.1 2120.38  4989.6 2115.78
  4990.2 2110.66  4990.8 2109.66  5017.7 2110.66  5028.1 2115.00  5033.2 2114.52
  5040.2 2118.82  5050.4 2119.45  5163.7 2119.62  5202.4 2123.24  5232.9 2121.14
  5271.2 2124.79  5293.7 2123.49  5314.0 2126.63  5425.5 2132.21  5445.8 2135.77
  5504.8 2153.23  5526.9 2159.67  5567.4 2160.09  5597.8 2171.95  5608.0 2172.51
#Mann=8,-1,0
  3350.5    0.07       0  3613.7    0.16       0  3702.6    0.07       0
  4550.1    0.16       0  4990.2    0.07       0  5017.7    0.16       0
  5163.7    0.07       0  5504.8    0.16       0
Bank Sta=4990.2,5017.7
Exp/Cntr=0.3,0.1

Type RM Length L Ch R = 1,68691,748,748,748
BEGIN DESCRIPTION:
Bitter Creek 60.0
END DESCRIPTION:
XS GIS Cut Line= 3
      1412355.00      6834288.04      1412560.18      6836288.44
      1412755.00      6836788.00
#Sta/Elev= 30
  2989.1 2169.23  3036.2 2170.49  3041.2 2168.06  3059.4 2171.27  3099.6 2172.37
  3160.0 2157.21  3202.7 2150.39  3243.6 2145.40  3391.2 2133.98  3626.8 2131.53
  3712.8 2123.99  3763.1 2130.18  3991.3 2128.52  4587.4 2126.66  4703.6 2121.01
  4802.9 2120.42  4848.8 2116.72  4924.7 2117.75  4959.3 2116.25  4978.0 2110.00
  4978.6 2109.00  5005.6 2110.00  5010.3 2117.89  5051.2 2122.98  5056.6 2125.98
  5237.7 2134.90  5321.5 2140.76  5363.7 2148.41  5418.1 2160.82  5536.2 2166.52
#Mann=9,-1,0
  2989.1    0.07       0  3202.7    0.16       0  3243.6    0.07       0
  3991.3    0.16       0  4924.7    0.12       0  4978.0    0.07       0
  5005.6    0.12       0  5237.7    0.07       0  5363.7    0.16       0
Bank Sta=4978,5005.6
Exp/Cntr=0.3,0.1

Type RM Length L Ch R = 1,67943,746,746,746
BEGIN DESCRIPTION:
Bitter Creek 59.0
END DESCRIPTION:
XS GIS Cut Line= 3
      1410517.10      6834205.87      1411861.02      6836240.49
      1412454.99      6836837.99
#Sta/Elev= 30
  2561.6 2192.62  2697.9 2187.01  2728.0 2184.05  2770.2 2172.53  2835.0 2166.61
  2980.1 2153.52  3023.0 2147.42  3103.5 2144.92  3131.4 2139.57  3175.4 2136.33
  3628.8 2129.28  4704.7 2125.21  4718.6 2125.59  4783.9 2124.30  4805.3 2115.82
  4820.0 2114.56  4905.0 2115.41  4973.0 2114.42  4983.6 2109.42  4984.2 2108.42
  5012.0 2109.42  5022.3 2113.28  5075.2 2117.05  5121.3 2121.14  5298.0 2123.74
  5545.5 2123.91  5708.2 2131.11  5764.7 2145.61  5807.2 2163.46  5842.5 2164.82
#Mann=10,-1,0
  2561.6    0.07       0  2835.0    0.16       0  2980.1    0.07       0
  3628.8    0.16       0  4704.7    0.07       0  4718.6    0.16       0
  4905.0    0.07       0  4983.6    0.07       0  5012.0    0.07       0
  5075.2    0.16       0
Bank Sta=4983.6,5012
Exp/Cntr=0.3,0.1

Type RM Length L Ch R = 1,67197,748,748,748
BEGIN DESCRIPTION:
Bitter Creek 58.0
END DESCRIPTION:
XS GIS Cut Line= 3
      1410617.80      6834521.85      1411749.29      6836940.35
      1412254.99      6836938.00
#Sta/Elev= 30
  2329.9 2164.81  2412.9 2157.17  2426.2 2156.32  2589.9 2143.13  2601.7 2140.48
  2623.8 2141.53  2656.9 2140.13  2678.9 2136.13  2709.6 2136.58  2812.0 2132.14
  2957.4 2130.17  3992.5 2124.60  4180.4 2123.71  4672.4 2121.13  4882.6 2117.60
  4973.9 2108.47  4980.2 2106.54  4981.0 2105.54  5015.8 2106.54  5025.7 2113.08
  5061.0 2114.83  5125.7 2116.29  5145.7 2120.79  5165.7 2128.83  5215.7 2143.92
  5255.7 2159.23  5265.7 2160.56  5295.7 2162.63  5385.7 2158.59  5505.7 2163.01
#Mann=10,-1,0
  2329.9    0.07       0  2412.9    0.16       0  2426.2    0.07       0
  2957.4    0.16       0  3992.5    0.07       0  4180.4    0.16       0
  4672.4    0.15       0  4980.2    0.07       0  5015.8    0.15       0
  5061.0    0.16       0
Bank Sta=4980.2,5015.8
Exp/Cntr=0.3,0.1

Type RM Length L Ch R = 1,66449,741,741,741
BEGIN DESCRIPTION:
Bitter Creek 57.0
END DESCRIPTION:
XS GIS Cut Line= 3
      1410677.31      6834878.33      1411230.00      6837388.40
      1412005.01      6837588.00
#Sta/Elev= 30
  2429.8 2139.32  2562.6 2133.82  2742.6 2131.14  3468.8 2126.73  3717.6 2125.35
  3967.9 2123.47  4138.2 2122.30  4364.7 2120.96  4456.9 2115.38  4620.7 2112.45
  4682.2 2116.40  4760.8 2115.77  4782.7 2115.93  4861.7 2112.83  4953.5 2112.32
  4976.9 2105.35  4977.7 2104.35  5012.5 2105.35  5019.5 2108.87  5055.1 2109.15
  5060.2 2111.69  5182.3 2118.16  5351.8 2119.68  5513.9 2120.35  5624.9 2122.57
  5686.7 2129.09  5707.4 2129.07  5736.7 2136.44  5741.8 2135.50  5800.3 2157.35
#Mann=13,-1,0
  2429.8    0.07       0  2742.6    0.16       0  3468.8    0.07       0
  3717.6    0.16       0  3967.9    0.07       0  4138.2    0.16       0
  4760.8    0.15       0  4782.7    0.16       0  4861.7    0.15       0
  4976.9    0.07       0  5012.5    0.15       0  5351.8   0.035       0
  5513.9    0.16       0
Bank Sta=4976.9,5012.5
Exp/Cntr=0.3,0.1

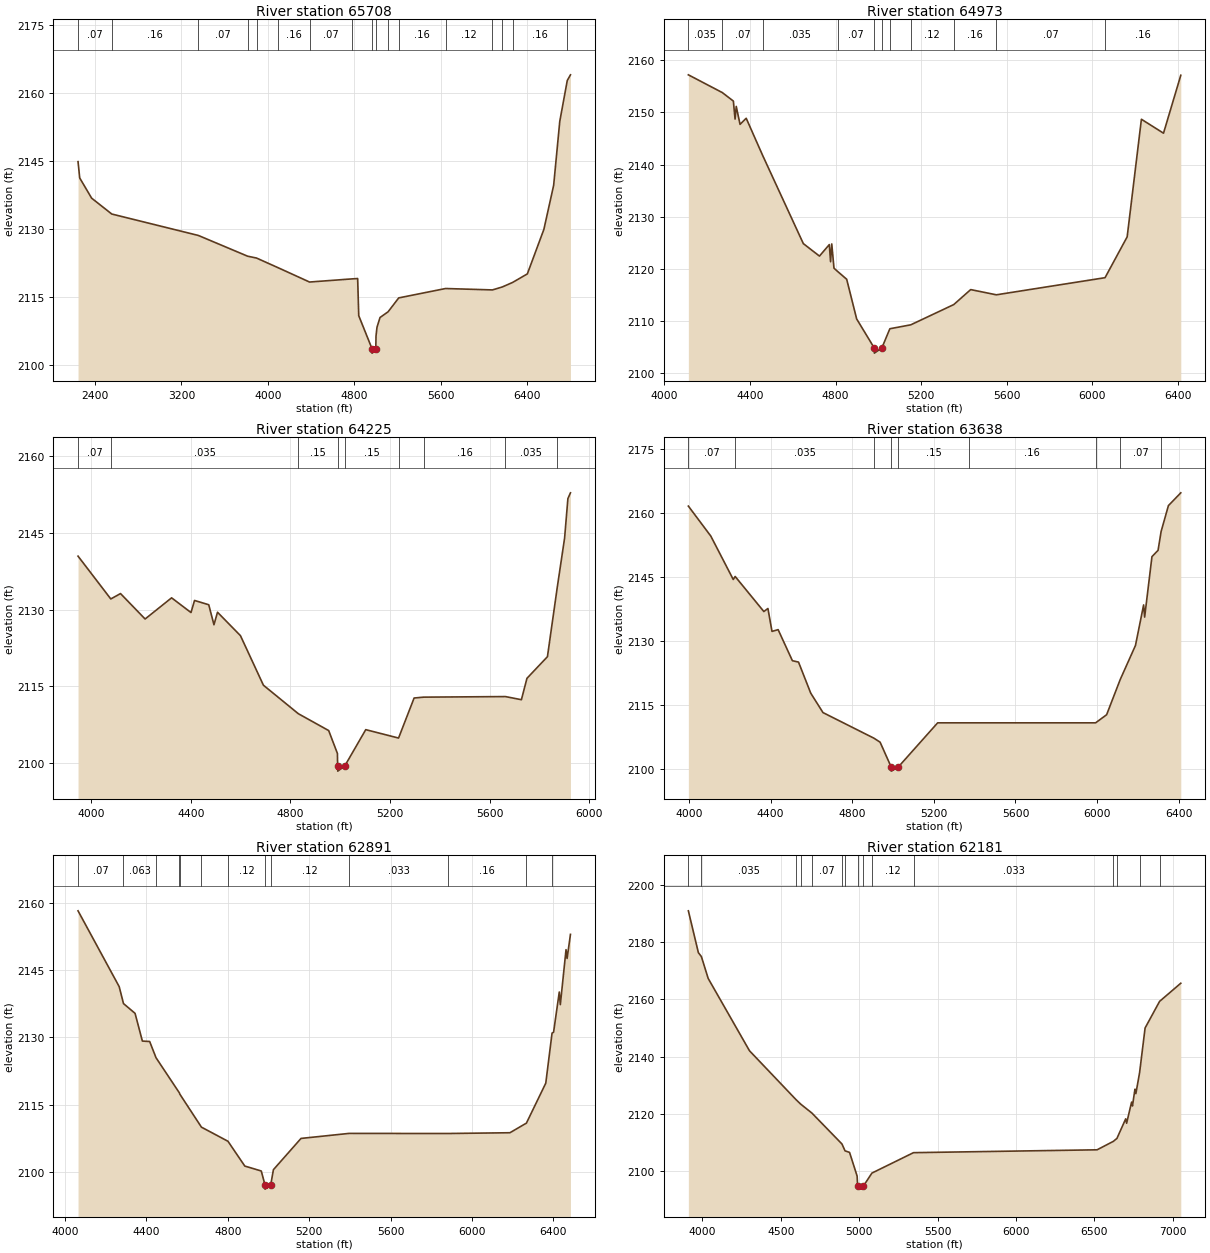
Type RM Length L Ch R = 1,65708,735,735,735
BEGIN DESCRIPTION:
Bitter Creek 56.0
END DESCRIPTION:
XS GIS Cut Line= 3
      1410651.99      6834802.39      1410584.58      6837557.76
      1412205.01      6838338.01
#Sta/Elev= 30
  2243.8 2144.85  2259.4 2141.25  2369.5 2136.80  2555.7 2133.30  3357.1 2128.57
  3812.2 2124.00  3894.8 2123.59  4096.1 2121.44  4385.0 2118.30  4776.6 2118.99
  4830.2 2119.07  4840.2 2110.88  4962.4 2103.62  4963.1 2102.62  4997.9 2103.62
  5000.0 2106.39  5009.0 2108.33  5037.2 2110.48  5111.9 2111.74  5210.0 2114.80
  5643.5 2116.87  6077.0 2116.56  6167.5 2117.21  6263.5 2118.21  6399.8 2120.10
  6552.6 2129.91  6643.1 2139.64  6699.5 2153.72  6769.0 2162.75  6798.5 2164.00
#Mann=17,-1,0
  2243.8    0.07       0  2555.7    0.16       0  3357.1    0.07       0
  3812.2    0.16       0  3894.8    0.07       0  4096.1    0.16       0
  4385.0    0.07       0  4776.6    0.15       0  4962.4    0.07       0
  4997.9    0.15       0  5111.9    0.12       0  5210.0    0.16       0
  5643.5    0.12       0  6077.0    0.16       0  6167.5    0.07       0
  6263.5    0.16       0  6769.0    0.07       0
Bank Sta=4962.4,4997.9
Exp/Cntr=0.3,0.1

Type RM Length L Ch R = 1,64973,748,748,748
BEGIN DESCRIPTION:
Bitter Creek 55.0
END DESCRIPTION:
XS GIS Cut Line= 3
      1409892.66      6837833.57      1410704.59      6838193.17
      1412105.00      6838388.00
#Sta/Elev= 30
  4112.0 2157.21  4270.6 2153.81  4322.4 2152.18  4330.3 2148.73  4335.8 2151.16
  4353.6 2147.72  4382.4 2148.89  4459.3 2141.77  4649.4 2124.88  4724.8 2122.49
  4770.8 2124.69  4776.8 2121.41  4782.3 2124.82  4792.7 2120.17  4809.8 2119.54
  4852.1 2118.05  4898.7 2110.45  4980.8 2104.90  4981.5 2103.90  5016.6 2104.90
  5053.9 2108.57  5151.6 2109.32  5352.6 2113.20  5431.8 2116.07  5551.7 2115.07
  6059.8 2118.35  6163.2 2126.17  6229.8 2148.70  6333.1 2146.03  6413.9 2157.13
#Mann=11,-1,0
  4112.0   0.035       0  4270.6    0.07       0  4459.3   0.035       0
  4809.8    0.07       0  4980.8    0.07       0  5016.6    0.07       0
  5053.9    0.15       0  5151.6    0.12       0  5352.6    0.16       0
  5551.7    0.07       0  6059.8    0.16       0
Bank Sta=4980.8,5016.6
Exp/Cntr=0.3,0.1

Type RM Length L Ch R = 1,64225,587,587,587
BEGIN DESCRIPTION:
Bitter Creek 54.0
END DESCRIPTION:
XS GIS Cut Line= 3
      1410105.00      6838188.00      1410905.00      6838873.00
      1411804.98      6839088.00
#Sta/Elev= 30
  3946.8 2140.41  4078.4 2132.06  4117.5 2133.11  4216.3 2128.15  4322.7 2132.28
  4400.7 2129.41  4414.9 2131.77  4472.0 2130.93  4492.9 2127.03  4507.2 2129.47
  4599.4 2124.90  4691.6 2115.24  4831.9 2109.68  4953.9 2106.39  4989.0 2101.92
  4989.8 2099.48  4990.4 2098.48  5018.4 2099.48  5102.8 2106.57  5234.6 2104.93
  5297.1 2112.74  5335.6 2112.91  5664.2 2113.02  5728.2 2112.41  5750.5 2116.58
  5832.8 2120.80  5872.6 2134.44  5901.7 2143.92  5915.0 2151.63  5925.3 2152.76
#Mann=9,-1,0
  3946.8    0.07       0  4078.4   0.035       0  4831.9    0.15       0
  4989.8    0.07       0  5018.4    0.15       0  5234.6    0.15       0
  5335.6    0.16       0  5664.2   0.035       0  5872.6    0.16       0
Bank Sta=4989.8,5018.4
Exp/Cntr=0.3,0.1

Type RM Length L Ch R = 1,63638,747,747,747
BEGIN DESCRIPTION:
Bitter Creek 53.0
END DESCRIPTION:
XS GIS Cut Line= 3
      1409605.04      6839338.00      1410608.54      6839339.46
      1412004.99      6839538.00
#Sta/Elev= 30
  3996.5 2161.52  4106.5 2154.50  4216.5 2144.34  4225.9 2145.04  4366.5 2136.83
  4386.5 2137.54  4406.5 2132.17  4436.5 2132.59  4506.5 2125.31  4536.5 2124.99
  4596.5 2117.70  4656.5 2113.16  4906.3 2107.16  4936.5 2106.23  4990.4 2100.45
  4991.2 2099.45  5026.2 2100.45  5218.6 2110.76  5371.0 2110.76  5992.9 2110.76
  6046.9 2112.66  6113.4 2120.88  6188.3 2128.88  6228.3 2138.38  6233.3 2135.53
  6269.1 2149.68  6299.1 2151.17  6314.1 2155.59  6349.9 2161.64  6410.5 2164.63
#Mann=9,-1,0
  3996.5    0.07       0  4225.9   0.035       0  4906.3    0.15       0
  4990.4    0.07       0  5026.2    0.15       0  5371.0    0.16       0
  5992.9   0.035       0  6113.4    0.07       0  6314.1   0.035       0
Bank Sta=4990.4,5026.2
Exp/Cntr=0.3,0.1

Type RM Length L Ch R = 1,62891,710,710,710
BEGIN DESCRIPTION:
Bitter Creek 52.0
END DESCRIPTION:
XS GIS Cut Line= 3
      1409605.00      6839488.00      1410381.73      6840011.36
      1411805.00      6839588.00
#Sta/Elev= 30
  4063.4 2158.26  4265.8 2141.33  4286.9 2137.55  4343.8 2135.37  4379.8 2129.18
  4415.7 2129.08  4446.9 2125.46  4562.2 2117.58  4564.0 2117.33  4670.2 2109.96
  4800.6 2106.81  4883.5 2101.27  4964.4 2100.17  4982.4 2097.12  4983.0 2096.12
  5011.1 2097.12  5024.2 2100.46  5159.9 2107.44  5395.8 2108.56  5882.5 2108.54
  6187.2 2108.71  6268.3 2110.86  6363.5 2119.78  6394.4 2130.96  6401.9 2131.16
  6429.9 2140.13  6435.1 2137.32  6463.1 2149.59  6468.3 2147.63  6484.9 2153.00
#Mann=13,-1,0
  4063.4    0.07       0  4286.9   0.063       0  4446.9   0.035       0
  4562.2    0.07       0  4564.0   0.035       0  4670.2   0.033       0
  4800.6    0.12       0  4982.4    0.07       0  5011.1    0.12       0
  5395.8   0.033       0  5882.5    0.16       0  6268.3   0.035       0
  6394.4    0.16       0
Bank Sta=4982.4,5011.1
Exp/Cntr=0.3,0.1

Type RM Length L Ch R = 1,62181,745,745,745
BEGIN DESCRIPTION:
Bitter Creek 51.0
END DESCRIPTION:
XS GIS Cut Line= 3
      1409155.04      6840987.99      1410177.86      6840611.53
      1411954.99      6839588.01
#Sta/Elev= 30
  3910.1 2190.87  3974.0 2176.26  3993.2 2174.89  4036.5 2167.26  4300.0 2142.01
  4596.5 2124.96  4626.1 2123.40  4697.6 2120.28  4889.8 2109.46  4909.2 2107.07
  4938.1 2106.53  4986.3 2098.29  4989.9 2094.70  4990.7 2093.70  5025.7 2094.70
  5080.7 2099.30  5346.0 2106.43  6517.0 2107.43  6621.0 2110.39  6643.7 2111.43
  6699.5 2118.25  6705.3 2116.70  6736.9 2124.08  6742.6 2122.73  6758.4 2128.60
  6764.2 2127.04  6788.1 2134.39  6823.1 2149.96  6915.6 2159.26  7050.8 2165.59
#Mann=15,-1,0
  3910.1    0.07       0  3993.2   0.035       0  4596.5    0.07       0
  4626.1   0.035       0  4697.6    0.07       0  4889.8   0.035       0
  4909.2   0.033       0  4989.9   0.033       0  5025.7   0.033       0
  5080.7    0.12       0  5346.0   0.033       0  6621.0    0.16       0
  6643.7   0.035       0  6788.1    0.16       0  6915.6   0.035       0
Bank Sta=4989.9,5025.7
Exp/Cntr=0.3,0.1

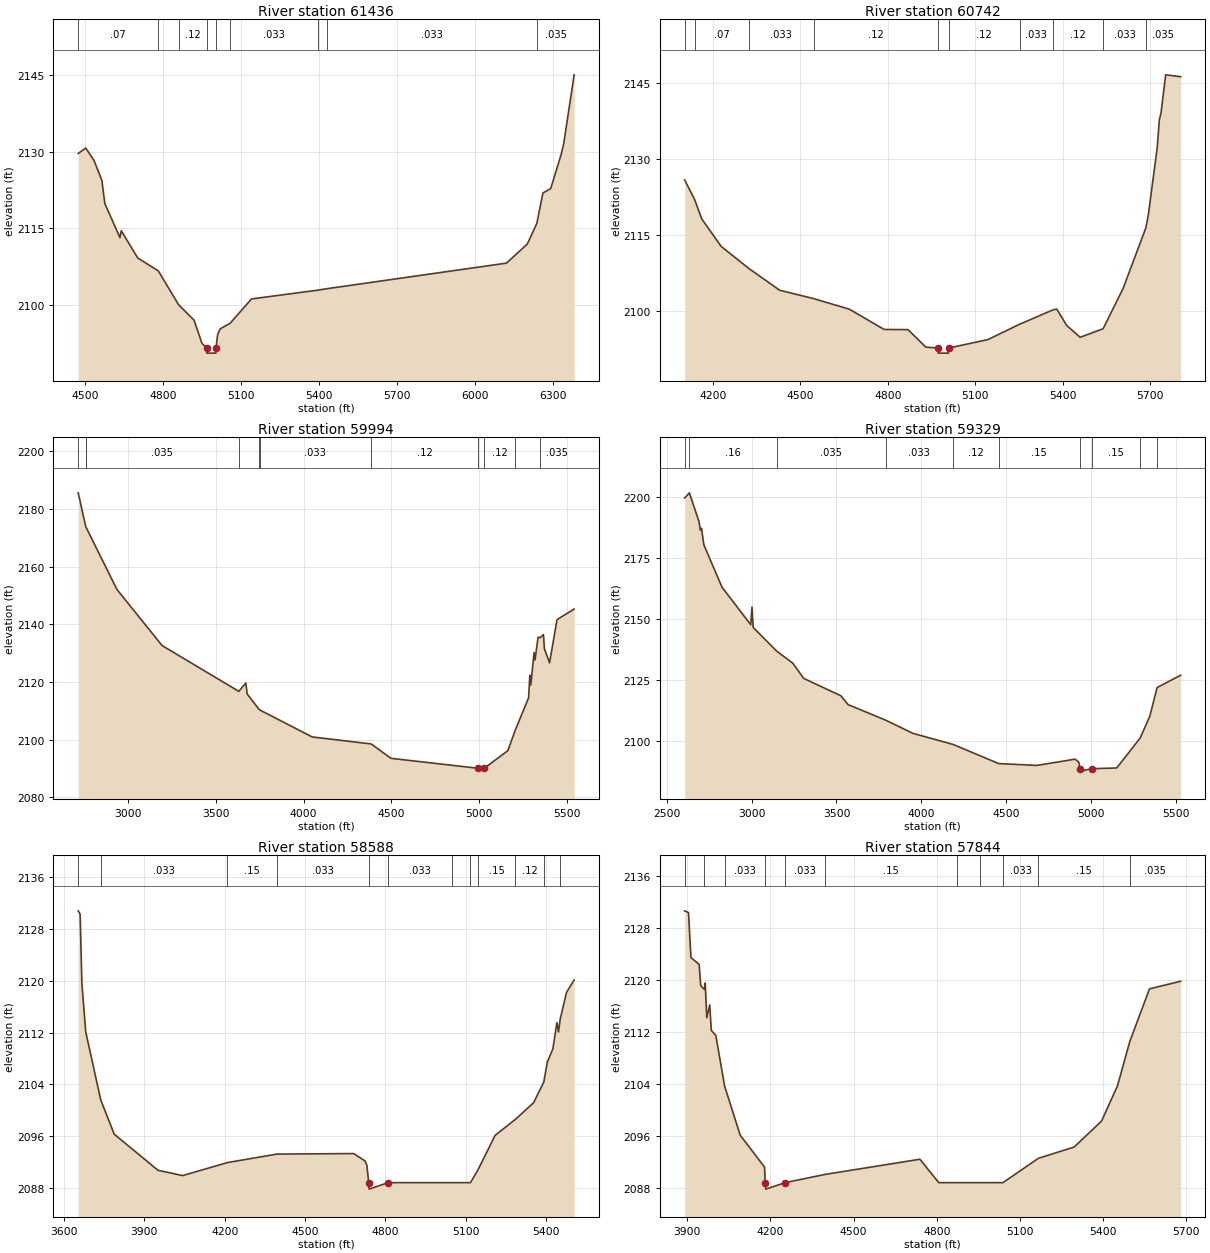
Type RM Length L Ch R = 1,61436,694,694,694
BEGIN DESCRIPTION:
Bitter Creek 50.0
END DESCRIPTION:
XS GIS Cut Line= 3
      1410105.03      6841238.00      1410625.49      6841157.80
      1412005.05      6841138.00
#Sta/Elev= 30
  4473.4 2129.62  4502.4 2130.69  4534.1 2128.27  4564.4 2124.37  4575.7 2119.85
  4633.9 2113.19  4638.9 2114.55  4702.1 2109.23  4781.5 2106.70  4859.2 2100.10
  4918.6 2097.09  4948.9 2092.58  4967.0 2091.65  4967.8 2090.65  5002.3 2090.65
  5003.1 2091.65  5009.5 2094.32  5019.5 2095.40  5057.5 2096.49  5139.5 2101.23
  5393.9 2102.94  5429.6 2103.23  6119.6 2108.22  6199.6 2111.94  6236.4 2116.00
  6259.6 2121.91  6289.6 2122.78  6329.6 2129.41  6339.6 2131.53  6379.7 2144.98
#Mann=9,-1,0
  4473.4    0.07       0  4781.5   0.033       0  4859.2    0.12       0
  4967.0    0.07       0  5003.1    0.12       0  5057.5   0.033       0
  5393.9    0.12       0  5429.6   0.033       0  6236.4   0.035       0
Bank Sta=4967,5003.1
Exp/Cntr=0.3,0.1

Type RM Length L Ch R = 1,60742,748,748,748
BEGIN DESCRIPTION:
Bitter Creek 49.0
END DESCRIPTION:
XS GIS Cut Line= 3
      1410005.01      6841388.00      1410804.62      6841793.16
      1411504.99      6842188.00
#Sta/Elev= 30
  4103.6 2125.93  4137.6 2122.08  4162.1 2118.25  4228.9 2112.80  4324.4 2108.42
  4429.4 2104.15  4545.6 2102.50  4668.7 2100.40  4787.4 2096.41  4869.2 2096.37
  4930.4 2092.92  4972.3 2092.73  4973.0 2091.73  5007.6 2091.73  5008.3 2092.73
  5143.1 2094.40  5251.8 2097.43  5366.3 2100.27  5379.3 2100.43  5413.7 2097.18
  5459.6 2094.86  5538.3 2096.55  5606.8 2104.50  5684.6 2116.44  5693.5 2119.08
  5723.7 2132.29  5731.1 2137.81  5736.8 2139.16  5752.7 2146.70  5804.0 2146.33
#Mann=10,-1,0
  4103.6   0.035       0  4137.6    0.07       0  4324.4   0.033       0
  4545.6    0.12       0  4972.3    0.07       0  5008.3    0.12       0
  5251.8   0.033       0  5366.3    0.12       0  5538.3   0.033       0
  5684.6   0.035       0
Bank Sta=4972.3,5008.3
Exp/Cntr=0.3,0.1

Type RM Length L Ch R = 1,59994,665,665,665
BEGIN DESCRIPTION:
Bitter Creek 48.0
END DESCRIPTION:
XS GIS Cut Line= 3
      1409155.03      6841088.03      1410955.01      6842493.01
      1411455.01      6842287.99
#Sta/Elev= 30
  2716.6 2185.63  2760.0 2173.79  2760.8 2173.74  2937.3 2152.10  3194.1 2132.67
  3630.9 2116.78  3670.8 2119.67  3678.9 2115.84  3743.2 2110.77  3750.0 2110.34
  4048.6 2100.97  4384.6 2098.54  4497.5 2093.55  4992.6 2090.11  4993.4 2089.11
  5028.7 2090.11  5162.8 2096.20  5206.0 2103.45  5281.0 2114.55  5288.2 2122.34
  5293.6 2118.98  5312.2 2130.25  5317.6 2127.66  5335.0 2135.59  5346.0 2135.36
  5365.6 2136.46  5371.0 2131.60  5400.3 2126.66  5442.9 2141.65  5540.4 2145.33
#Mann=11,-1,0
  2716.6    0.07       0  2760.0    0.16       0  2760.8   0.035       0
  3630.9    0.07       0  3743.2   0.035       0  3750.0   0.033       0
  4384.6    0.12       0  4992.6    0.07       0  5028.7    0.12       0
  5206.0   0.033       0  5346.0   0.035       0
Bank Sta=4992.6,5028.7
Exp/Cntr=0.3,0.1

Type RM Length L Ch R = 1,59329,741,741,741
BEGIN DESCRIPTION:
Bitter Creek 47.0
END DESCRIPTION:
XS GIS Cut Line= 3
      1408954.99      6841087.99      1410534.92      6842887.81
      1411054.96      6842987.99
#Sta/Elev= 30
  2605.1 2199.44  2632.8 2201.54  2690.0 2189.68  2697.6 2186.31  2704.3 2187.04
  2718.5 2180.27  2824.8 2163.05  2994.7 2147.64  3002.2 2154.88  3008.9 2146.55
  3148.2 2136.84  3243.3 2131.90  3306.8 2125.73  3526.1 2118.63  3568.7 2115.02
  3790.3 2108.66  3951.2 2103.27  4186.8 2098.77  4456.7 2090.93  4680.9 2090.17
  4907.7 2092.73  4929.5 2091.43  4936.1 2088.84  4937.6 2087.84  5008.2 2088.84
  5152.8 2089.13  5290.6 2101.32  5348.0 2110.27  5390.8 2121.98  5529.6 2127.02
#Mann=10,-1,0
  2605.1    0.07       0  2632.8    0.16       0  3148.2   0.035       0
  3790.3   0.033       0  4186.8    0.12       0  4456.7    0.15       0
  4936.1    0.07       0  5008.2    0.15       0  5290.6   0.035       0
  5390.8   0.063       0
Bank Sta=4936.1,5008.2
Exp/Cntr=0.3,0.1

Type RM Length L Ch R = 1,58588,744,744,744
BEGIN DESCRIPTION:
Bitter Creek 46.0
END DESCRIPTION:
XS GIS Cut Line= 3
      1409604.98      6844488.02      1410488.19      6843471.39
      1410904.98      6843188.01
#Sta/Elev= 30
  3653.3 2130.81  3660.5 2130.27  3667.1 2119.60  3681.3 2112.14  3737.3 2101.63
  3787.7 2096.32  3951.0 2090.75  4043.1 2089.93  4210.2 2091.94  4395.3 2093.25
  4681.3 2093.33  4724.0 2092.18  4730.6 2091.52  4737.3 2088.84  4738.8 2087.84
  4809.5 2088.84  5049.5 2088.84  5117.1 2088.84  5146.7 2090.94  5209.2 2096.15
  5284.4 2098.60  5352.9 2101.19  5390.8 2104.39  5403.7 2107.43  5424.7 2109.50
  5439.6 2113.55  5445.7 2112.12  5451.8 2114.06  5475.6 2118.22  5504.0 2120.14
#Mann=12,-1,0
  3653.3   0.035       0  3737.3   0.033       0  4210.2    0.15       0
  4395.3   0.033       0  4737.3   0.033       0  4809.5   0.033       0
  5049.5    0.15       0  5117.1   0.033       0  5146.7    0.15       0
  5284.4    0.12       0  5390.8   0.035       0  5451.8   0.063       0
Bank Sta=4737.3,4809.5
Exp/Cntr=0.3,0.1

Type RM Length L Ch R = 1,57844,737,737,737
BEGIN DESCRIPTION:
Bitter Creek 45.0
END DESCRIPTION:
XS GIS Cut Line= 3
      1409655.04      6844687.98      1410635.14      6844168.20
      1411254.96      6843888.02
#Sta/Elev= 30
  3890.6 2130.68  3904.4 2130.41  3913.2 2123.48  3942.7 2122.44  3948.4 2119.16
  3961.8 2118.58  3964.7 2119.58  3970.4 2114.22  3981.0 2116.20  3986.7 2112.28
  4003.0 2111.50  4034.6 2103.72  4091.0 2096.14  4178.9 2091.23  4181.2 2088.84
  4182.7 2087.84  4253.4 2088.84  4396.6 2090.10  4739.5 2092.44  4807.4 2088.84
  4874.2 2088.84  4958.0 2088.84  5039.2 2088.84  5166.8 2092.58  5296.1 2094.32
  5394.9 2098.32  5452.4 2103.74  5497.0 2110.59  5568.0 2118.67  5680.2 2119.84
#Mann=11,-1,0
  3890.6   0.063       0  3961.8   0.035       0  4034.6   0.033       0
  4181.2    0.07       0  4253.4   0.033       0  4396.6    0.15       0
  4874.2   0.033       0  4958.0    0.15       0  5039.2   0.033       0
  5166.8    0.15       0  5497.0   0.035       0
Bank Sta=4181.2,4253.4
Exp/Cntr=0.3,0.1