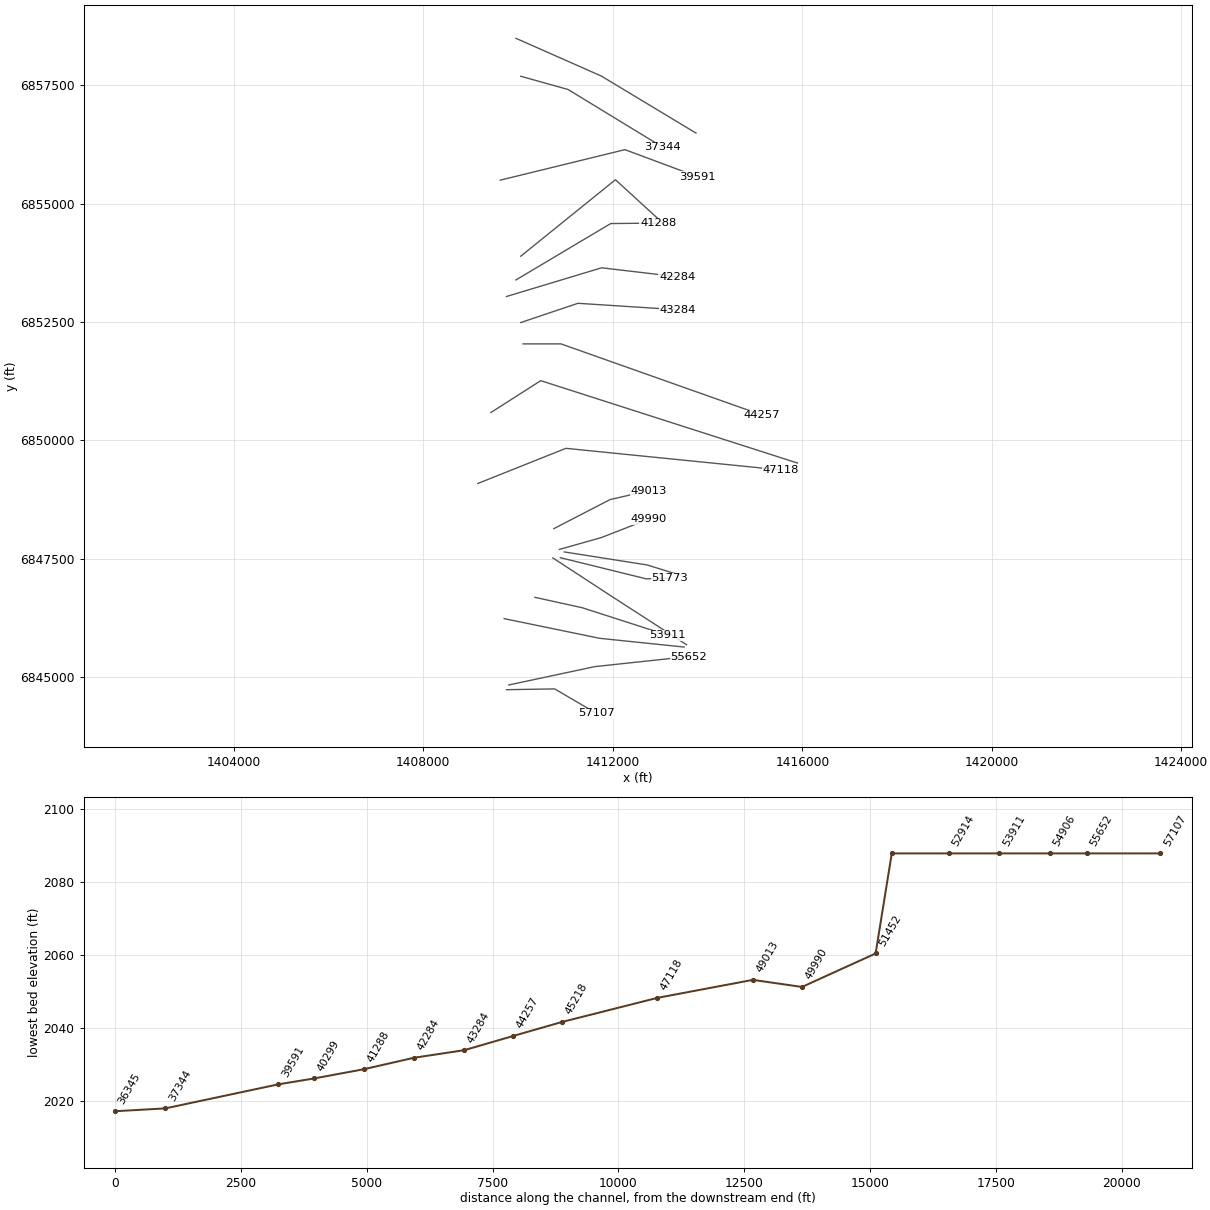
HEC-RAS study Bitter Creek.prj: Bitter Creek Base Level Engineering

--- Bitter Creek.g01 (geometry) --- (continued)

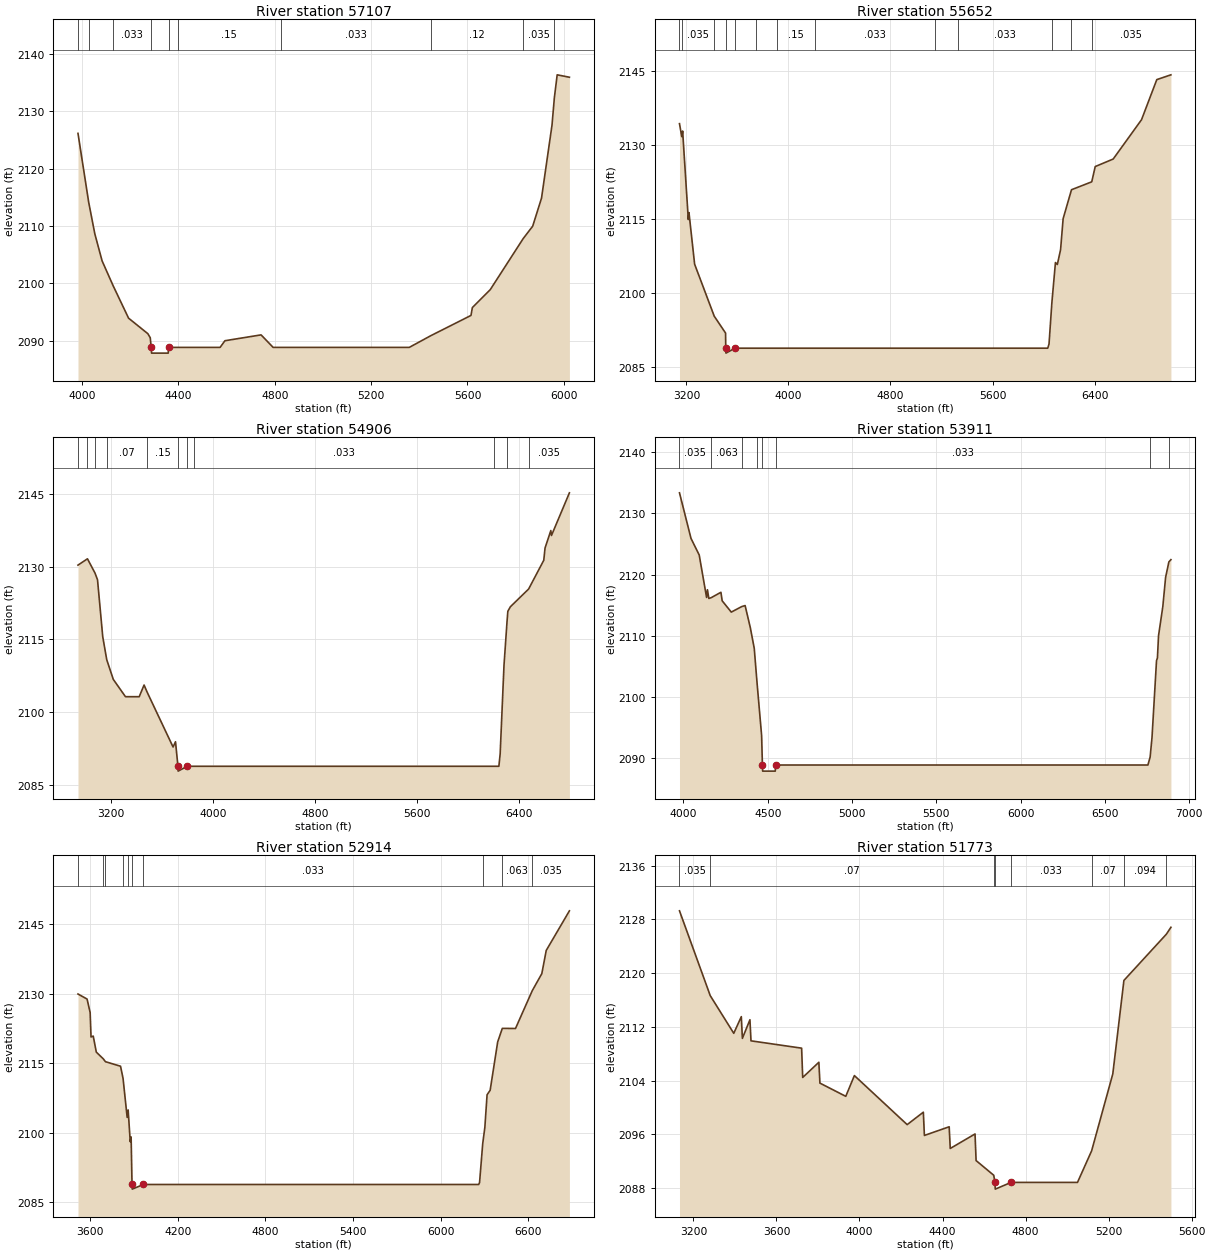
Type RM Length L Ch R = 1,57107,1455,1455,1455
BEGIN DESCRIPTION:
Bitter Creek 44.0
END DESCRIPTION:
XS GIS Cut Line= 3
      1409755.04      6844738.00      1410771.70      6844754.65
      1411655.00      6844238.00
#Sta/Elev= 30
  3983.2 2126.14  4027.7 2114.12  4053.2 2108.61  4083.2 2103.93  4129.4 2099.56
  4193.2 2093.93  4273.2 2091.23  4283.2 2090.52  4287.1 2088.84  4288.6 2087.84
  4357.8 2087.84  4359.3 2088.84  4397.7 2088.84  4573.2 2088.84  4593.2 2090.00
  4743.3 2091.02  4793.3 2088.84  4825.2 2088.84  5358.5 2088.84  5448.4 2090.89
  5614.7 2094.41  5620.4 2095.78  5694.8 2098.91  5831.4 2107.80  5870.8 2109.96
  5907.5 2114.85  5951.0 2127.56  5960.8 2132.34  5972.5 2136.34  6023.3 2135.92
#Mann=10,-1,0
  3983.2   0.063       0  4027.7   0.035       0  4129.4   0.033       0
  4287.1   0.033       0  4359.3   0.033       0  4397.7    0.15       0
  4825.2   0.033       0  5448.4    0.12       0  5831.4   0.035       0
  5960.8   0.063       0
Bank Sta=4287.1,4359.3
Exp/Cntr=0.3,0.1

Type RM Length L Ch R = 1,55652,746,746,746
BEGIN DESCRIPTION:
Bitter Creek 43.0
END DESCRIPTION:
XS GIS Cut Line= 3
      1409805.04      6844838.01      1411618.14      6845224.80
      1413605.03      6845438.00
#Sta/Elev= 30
  3146.1 2134.27  3163.9 2131.64  3170.8 2132.78  3215.2 2114.87  3220.4 2116.27
  3264.8 2105.83  3418.4 2095.32  3507.3 2091.90  3508.7 2088.84  3510.2 2087.84
  3580.9 2088.84  3747.0 2088.84  3913.0 2088.84  4211.0 2088.84  5150.0 2088.84
  5328.9 2088.84  6032.8 2088.84  6042.8 2089.69  6065.0 2098.00  6093.1 2106.17
  6108.0 2105.78  6133.3 2108.76  6153.4 2115.04  6218.9 2120.90  6377.7 2122.50
  6404.9 2125.59  6545.7 2127.11  6768.0 2135.07  6887.6 2143.18  6998.3 2144.15
#Mann=13,-1,0
  3146.1   0.063       0  3163.9   0.035       0  3418.4   0.033       0
  3508.7   0.033       0  3580.9   0.033       0  3747.0   0.033       0
  3913.0    0.15       0  4211.0   0.033       0  5150.0    0.15       0
  5328.9   0.033       0  6065.0   0.035       0  6218.9   0.063       0
  6377.7   0.035       0
Bank Sta=3508.7,3580.9
Exp/Cntr=0.3,0.1

Type RM Length L Ch R = 1,54906,995,995,995
BEGIN DESCRIPTION:
Bitter Creek 42.0
END DESCRIPTION:
XS GIS Cut Line= 3
      1409705.02      6846238.00      1411720.99      6845822.70
      1413504.96      6845638.00
#Sta/Elev= 30
  2941.7 2130.33  3016.0 2131.63  3075.1 2128.69  3094.8 2127.31  3135.7 2115.57
  3167.1 2110.82  3218.4 2106.76  3313.9 2103.19  3421.5 2103.19  3459.7 2105.60
  3481.8 2104.24  3687.0 2092.81  3706.1 2093.90  3725.2 2088.84  3726.7 2087.84
  3797.8 2088.84  3852.8 2088.84  6204.6 2088.84  6240.6 2088.84  6250.7 2091.40
  6280.8 2109.67  6304.5 2118.68  6311.0 2120.82  6331.1 2121.75  6473.8 2125.40
  6592.5 2131.33  6602.5 2133.86  6647.8 2137.46  6652.9 2136.44  6793.5 2145.24
#Mann=11,-1,0
  2941.7   0.035       0  3016.0    0.07       0  3075.1    0.12       0
  3167.1    0.07       0  3481.8    0.15       0  3725.2   0.033       0
  3797.8    0.15       0  3852.8   0.033       0  6204.6    0.07       0
  6304.5   0.063       0  6473.8   0.035       0
Bank Sta=3725.2,3797.8
Exp/Cntr=0.3,0.1

Type RM Length L Ch R = 1,53911,997,997,997
BEGIN DESCRIPTION:
Bitter Creek 41.0
END DESCRIPTION:
XS GIS Cut Line= 3
      1410354.96      6846688.01      1411354.57      6846467.67
      1413154.95      6845888.02
#Sta/Elev= 30
  3976.4 2133.36  4044.6 2125.91  4093.4 2123.19  4137.1 2116.25  4142.2 2117.51
  4150.5 2116.08  4164.4 2116.21  4222.2 2117.09  4229.6 2115.70  4283.6 2113.85
  4345.4 2114.75  4365.6 2114.92  4396.3 2111.34  4419.8 2107.93  4435.9 2102.46
  4463.5 2093.68  4468.3 2088.84  4469.8 2087.84  4544.6 2087.84  4546.1 2088.84
  6754.9 2088.84  6768.1 2090.14  6779.2 2093.34  6806.0 2105.92  6811.3 2106.33
  6817.9 2109.98  6843.3 2114.75  6859.9 2119.54  6879.2 2122.05  6891.4 2122.43
#Mann=8,-1,0
  3976.4   0.035       0  4164.4   0.063       0  4345.4   0.035       0
  4435.9   0.033       0  4468.3   0.033       0  4546.1   0.033       0
  6768.1    0.07       0  6879.2   0.063       0
Bank Sta=4468.3,4546.1
Exp/Cntr=0.3,0.1

Type RM Length L Ch R = 1,52914,1141,1141,1141
BEGIN DESCRIPTION:
Bitter Creek 40.0
END DESCRIPTION:
XS GIS Cut Line= 3
      1410732.61      6847520.09      1411975.02      6846708.86
      1413555.01      6845687.99
#Sta/Elev= 30
  3516.2 2129.90  3578.4 2128.81  3599.5 2125.90  3605.5 2120.64  3620.6 2120.83
  3641.7 2117.37  3689.5 2115.92  3704.3 2115.31  3807.6 2114.33  3824.8 2111.71
  3852.9 2103.31  3859.7 2104.91  3874.0 2098.06  3880.0 2099.09  3886.2 2088.84
  3887.7 2087.84  3964.0 2088.84  6259.9 2088.84  6265.9 2089.27  6287.4 2097.62
  6302.2 2101.18  6317.3 2108.18  6338.4 2109.15  6389.9 2119.57  6421.6 2122.49
  6512.0 2122.47  6626.5 2130.60  6692.1 2134.29  6722.4 2139.29  6881.1 2147.83
#Mann=10,-1,0
  3516.2   0.035       0  3689.5   0.063       0  3704.3   0.094       0
  3824.8    0.07       0  3859.7   0.033       0  3886.2   0.033       0
  3964.0   0.033       0  6287.4    0.07       0  6421.6   0.063       0
  6626.5   0.035       0
Bank Sta=3886.2,3964
Exp/Cntr=0.3,0.1

Type RM Length L Ch R = 1,51773,321,321,321
BEGIN DESCRIPTION:
Bitter Creek 39.0
END DESCRIPTION:
XS GIS Cut Line= 3
      1410892.24      6847524.56      1412704.95      6847078.02
      1413204.95      6847088.00
#Sta/Elev= 30
  3133.1 2129.26  3281.3 2116.63  3394.5 2111.03  3430.9 2113.51  3436.0 2110.28
  3472.4 2113.05  3477.5 2109.91  3721.4 2108.82  3726.5 2104.46  3804.4 2106.72
  3809.5 2103.62  3934.0 2101.65  3975.5 2104.74  4229.7 2097.44  4307.6 2099.29
  4312.7 2095.83  4432.1 2097.12  4437.2 2093.89  4556.6 2096.05  4561.7 2092.09
  4646.8 2089.90  4652.5 2088.84  4654.0 2087.84  4730.3 2088.84  5050.1 2088.84
  5118.2 2093.54  5220.1 2104.98  5273.7 2118.90  5478.1 2125.78  5500.1 2126.81
#Mann=8,-1,0
  3133.1   0.035       0  3281.3    0.07       0  4646.8   0.033       0
  4652.5   0.033       0  4730.3   0.033       0  5118.2    0.07       0
  5273.7   0.094       0  5478.1   0.063       0
Bank Sta=4652.5,4730.3
Exp/Cntr=0.3,0.1

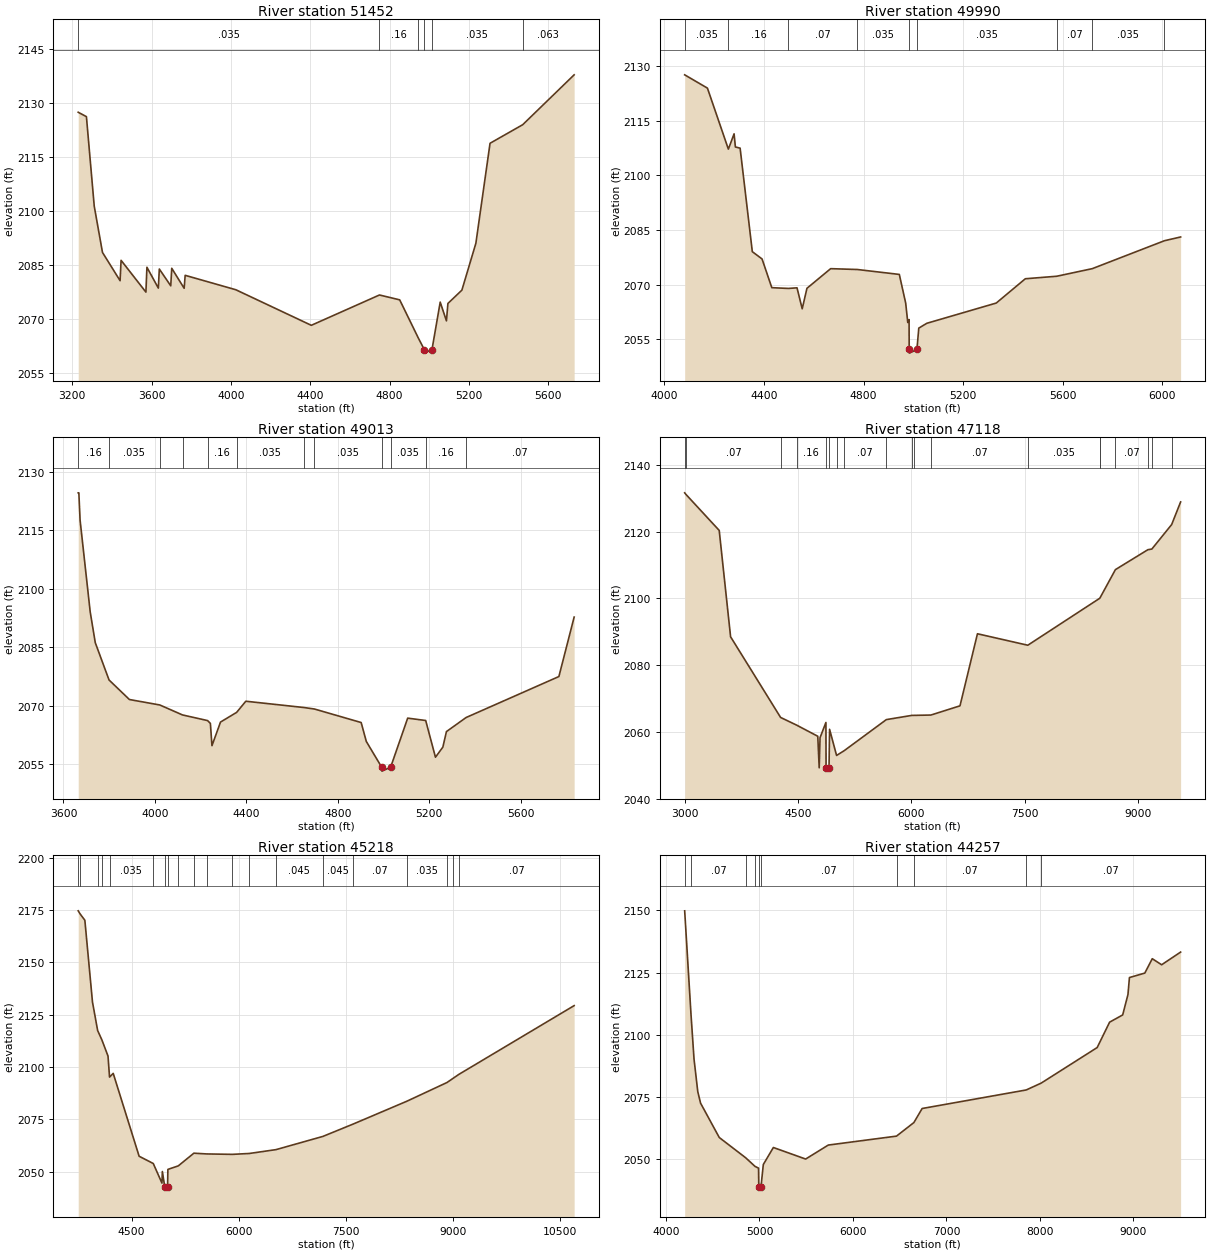
Type RM Length L Ch R = 1,51452,1462,1462,1462
BEGIN DESCRIPTION:
Bitter Creek 38.0
END DESCRIPTION:
XS GIS Cut Line= 3
      1410974.06      6847646.16      1412722.11      6847371.51
      1413420.07      6847155.55
#Sta/Elev= 30
  3230.5 2127.44  3271.9 2126.22  3311.3 2101.30  3352.9 2088.43  3441.6 2080.57
  3446.6 2086.24  3571.8 2077.39  3576.9 2084.31  3634.4 2078.51  3639.4 2083.82
  3697.0 2079.14  3702.0 2084.02  3764.6 2078.46  3769.7 2082.06  4025.0 2078.05
  4405.6 2068.15  4749.1 2076.59  4851.1 2075.24  4945.2 2064.60  4975.1 2061.41
  4975.9 2060.41  5014.0 2061.41  5055.4 2074.61  5086.8 2069.39  5094.2 2074.23
  5164.7 2077.94  5235.2 2090.99  5306.6 2118.81  5471.3 2123.98  5730.6 2137.86
#Mann=6,-1,0
  3230.5   0.035       0  4749.1    0.16       0  4945.2   0.035       0
  4975.1   0.035       0  5014.0   0.035       0  5471.3   0.063       0
Bank Sta=4975.1,5014
Exp/Cntr=0.3,0.1

Type RM Length L Ch R = 1,49990,977,977,977
BEGIN DESCRIPTION:
Bitter Creek 37.0
END DESCRIPTION:
XS GIS Cut Line= 3
      1410870.66      6847698.57      1411754.49      6847948.17
      1412755.03      6848338.01
#Sta/Elev= 30
  4081.6 2127.64  4173.0 2123.99  4257.1 2107.24  4280.1 2111.44  4285.3 2107.83
  4304.3 2107.51  4353.3 2079.09  4392.4 2077.09  4431.6 2069.20  4498.5 2068.99
  4532.9 2069.16  4553.7 2063.40  4572.8 2069.03  4668.0 2074.42  4774.9 2074.19
  4943.8 2072.84  4969.4 2064.97  4977.8 2059.64  4983.0 2060.44  4983.5 2052.23
  4984.1 2051.23  5014.6 2052.23  5022.0 2058.10  5054.2 2059.42  5333.2 2064.98
  5450.0 2071.65  5576.2 2072.34  5718.8 2074.42  6008.8 2082.09  6073.8 2083.12
#Mann=9,-1,0
  4081.6   0.035       0  4257.1    0.16       0  4498.5    0.07       0
  4774.9   0.035       0  4983.5   0.035       0  5014.6   0.035       0
  5576.2    0.07       0  5718.8   0.035       0  6008.8    0.07       0
Bank Sta=4983.5,5014.6
Exp/Cntr=0.3,0.1

Type RM Length L Ch R = 1,49013,1895,1895,1895
BEGIN DESCRIPTION:
Bitter Creek 36.0
END DESCRIPTION:
XS GIS Cut Line= 3
      1410755.04      6848138.02      1411941.43      6848751.24
      1412754.97      6848937.99
#Sta/Elev= 30
  3664.5 2124.64  3667.3 2124.64  3672.7 2117.63  3717.0 2094.05  3739.2 2086.15
  3799.4 2076.58  3888.5 2071.56  4021.4 2070.16  4120.9 2067.60  4230.7 2066.15
  4242.9 2065.42  4249.8 2059.71  4287.2 2065.77  4357.8 2068.26  4397.9 2071.12
  4651.5 2069.51  4698.3 2069.12  4902.7 2065.65  4925.2 2060.79  4992.6 2054.17
  4993.4 2053.17  5031.6 2054.17  5106.3 2066.78  5185.1 2066.17  5227.8 2056.74
  5260.2 2059.34  5275.8 2063.32  5362.0 2066.94  5767.9 2077.46  5834.7 2092.73
#Mann=12,-1,0
  3664.5    0.16       0  3799.4   0.035       0  4021.4    0.16       0
  4120.9    0.07       0  4230.7    0.16       0  4357.8   0.035       0
  4651.5    0.07       0  4698.3   0.035       0  4992.6   0.035       0
  5031.6   0.035       0  5185.1    0.16       0  5362.0    0.07       0
Bank Sta=4992.6,5031.6
Exp/Cntr=0.3,0.1

Type RM Length L Ch R = 1,47118,1900,1900,1900
BEGIN DESCRIPTION:
Bitter Creek 35.1
END DESCRIPTION:
XS GIS Cut Line= 3
      1409150.26      6849091.32      1411010.01      6849833.02
      1415551.49      6849376.19
#Sta/Elev= 30
  2997.8 2131.65  3015.6 2131.15  3455.1 2120.38  3605.8 2088.50  4267.9 2064.33
  4480.6 2062.02  4760.1 2058.69  4778.9 2049.24  4790.1 2058.26  4867.9 2062.82
  4870.0 2049.24  4870.8 2048.24  4909.0 2049.24  4916.4 2060.77  5009.0 2052.94
  5108.8 2054.35  5668.0 2063.68  6006.9 2064.95  6033.7 2064.95  6258.1 2065.05
  6643.2 2067.81  6874.4 2089.41  7541.0 2085.97  8493.2 2100.04  8501.5 2100.35
  8701.0 2108.63  9130.6 2114.60  9183.6 2114.80  9445.8 2122.14  9564.4 2128.92
#Mann=19,-1,0
  2997.8   0.035       0  3015.6    0.07       0  4267.9   0.035       0
  4480.6    0.16       0  4870.0    0.07       0  4909.0    0.16       0
  5009.0   0.045       0  5108.8    0.07       0  5668.0   0.045       0
  6006.9    0.07       0  6033.7   0.045       0  6258.1    0.07       0
  7541.0   0.035       0  8493.2    0.07       0  8501.5    0.16       0
  8701.0    0.07       0  9130.6    0.16       0  9183.6    0.07       0
  9445.8    0.16       0
Bank Sta=4870,4909
Exp/Cntr=0.3,0.1

Type RM Length L Ch R = 1,45218,961,961,961
BEGIN DESCRIPTION:
Bitter Creek 35.0
END DESCRIPTION:
XS GIS Cut Line= 3
      1409426.63      6850589.76      1410478.27      6851261.36
      1415898.37      6849522.48
#Sta/Elev= 30
  3752.2 2174.57  3777.2 2173.18  3845.2 2170.06  3952.0 2130.97  4024.3 2117.36
  4082.8 2112.97  4169.2 2105.19  4190.7 2095.14  4242.0 2096.91  4604.6 2057.32
  4802.7 2053.85  4923.9 2044.50  4929.8 2050.02  4963.6 2042.61  4964.3 2041.61
  5002.7 2042.61  5007.1 2051.03  5152.7 2052.72  5370.6 2058.78  5550.6 2058.42
  5909.5 2058.22  6145.8 2058.64  6519.9 2060.48  7175.8 2066.79  7600.2 2072.70
  8351.5 2083.61  8912.0 2092.53  8992.5 2094.41  9077.9 2096.41 10692.2 2129.28
#Mann=20,-1,0
  3752.2    0.07       0  3777.2    0.16       0  4024.3    0.07       0
  4082.8    0.16       0  4190.7   0.035       0  4802.7    0.16       0
  4963.6    0.07       0  5002.7    0.16       0  5152.7   0.035       0
  5370.6   0.045       0  5550.6    0.07       0  5909.5   0.045       0
  6145.8    0.07       0  6519.9   0.045       0  7175.8   0.045       0
  7600.2    0.07       0  8351.5   0.035       0  8912.0    0.07       0
  8992.5   0.035       0  9077.9    0.07       0
Bank Sta=4963.6,5002.7
Exp/Cntr=0.3,0.1

Type RM Length L Ch R = 1,44257,973,973,973
BEGIN DESCRIPTION:
Bitter Creek 34.0
END DESCRIPTION:
XS GIS Cut Line= 3
      1410105.02      6852038.00      1410904.92      6852038.03
      1415150.87      6850535.07
#Sta/Elev= 30
  4200.1 2149.86  4267.5 2108.28  4300.1 2090.18  4340.1 2077.08  4370.1 2072.43
  4570.1 2058.59  4852.9 2050.42  4951.9 2046.98  4990.1 2046.26  4992.9 2038.81
  4993.4 2037.81  5016.4 2038.81  5041.1 2047.73  5148.6 2054.57  5494.0 2049.92
  5735.8 2055.55  6465.5 2059.15  6651.4 2064.61  6739.8 2070.27  7853.2 2077.74
  8013.1 2080.50  8611.7 2094.81  8744.7 2105.03  8884.4 2107.94  8940.9 2116.16
  8956.9 2123.00  9121.0 2124.79  9200.9 2130.58  9301.1 2128.14  9504.1 2133.25
#Mann=10,-1,0
  4200.1   0.035       0  4267.5    0.07       0  4852.9    0.16       0
  4951.9    0.07       0  4992.9    0.07       0  5016.4    0.07       0
  6465.5   0.035       0  6651.4    0.07       0  7853.2   0.035       0
  8013.1    0.07       0
Bank Sta=4992.9,5016.4
Exp/Cntr=0.3,0.1

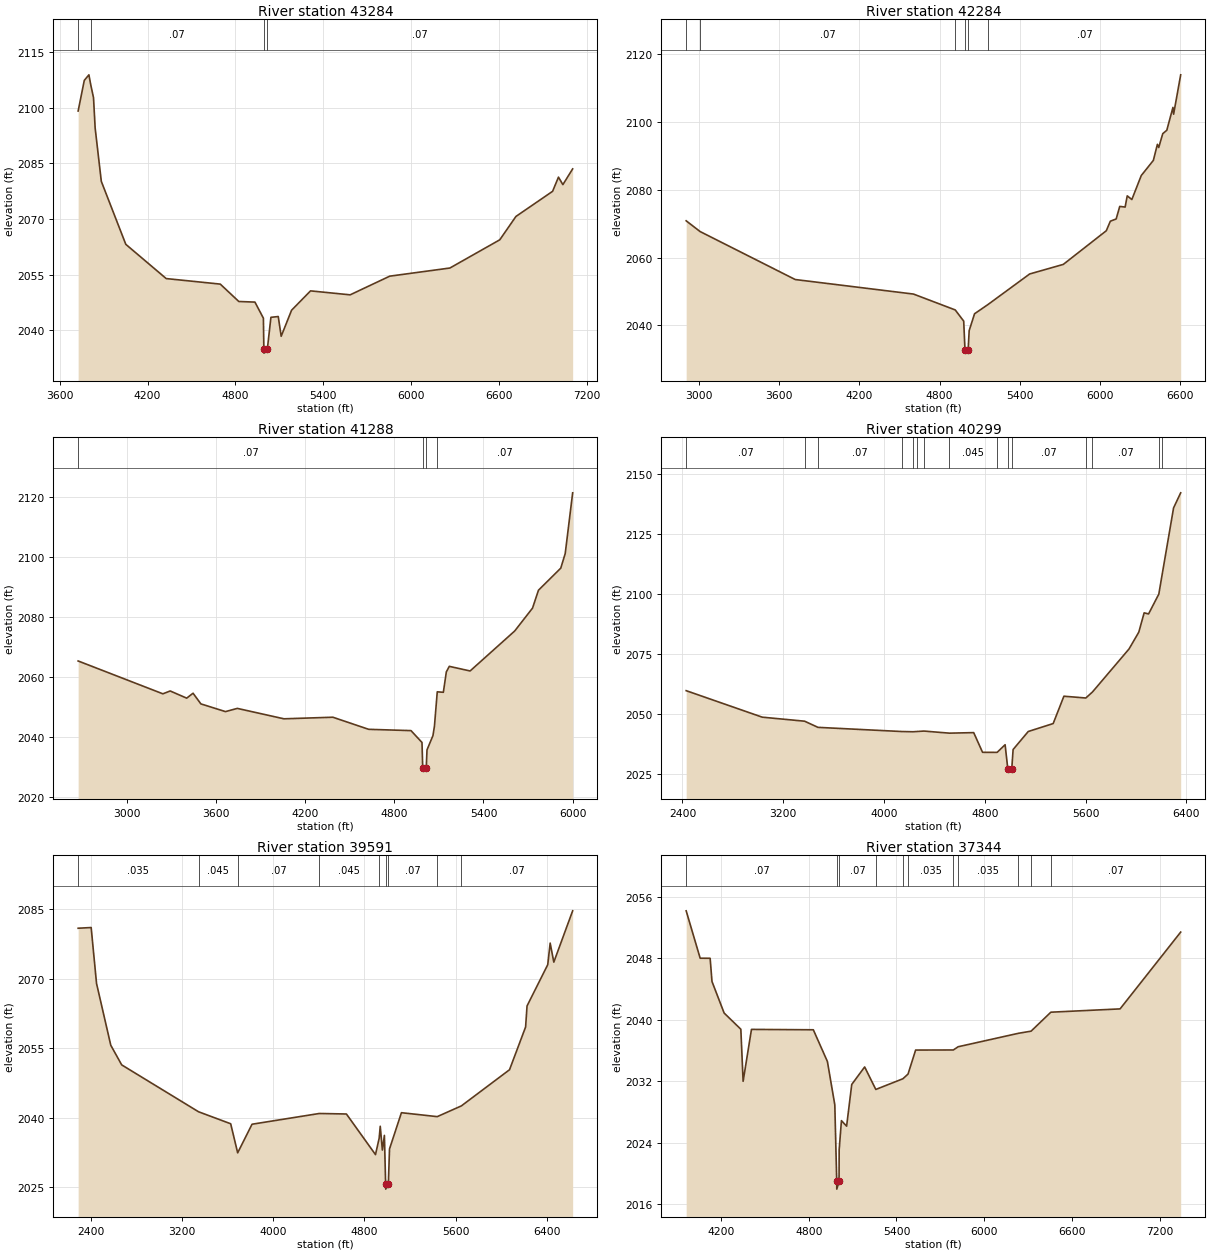
Type RM Length L Ch R = 1,43284,1000,1000,1000
BEGIN DESCRIPTION:
Bitter Creek 33.0
END DESCRIPTION:
XS GIS Cut Line= 3
      1410054.96      6852487.99      1411262.59      6852894.47
      1413361.68      6852759.97
#Sta/Elev= 30
  3725.8 2099.08  3767.8 2107.32  3799.3 2108.82  3811.6 2106.20  3830.8 2102.67
  3841.9 2094.53  3884.1 2080.14  4051.3 2063.19  4327.3 2053.97  4696.6 2052.48
  4823.2 2047.80  4933.3 2047.64  4991.1 2043.31  4994.3 2034.90  4994.8 2033.90
  5017.8 2034.90  5042.5 2043.54  5092.6 2043.75  5112.6 2038.44  5183.6 2045.45
  5313.1 2050.66  5583.6 2049.59  5854.2 2054.62  6265.0 2056.81  6605.7 2064.41
  6715.9 2070.69  6966.4 2077.46  7006.5 2081.28  7036.6 2079.26  7103.4 2083.50
#Mann=4,-1,0
  3725.8    0.16       0  3811.6    0.07       0  4994.3    0.07       0
  5017.8    0.07       0
Bank Sta=4994.3,5017.8
Exp/Cntr=0.3,0.1

Type RM Length L Ch R = 1,42284,996,996,996
BEGIN DESCRIPTION:
Bitter Creek 32.0
END DESCRIPTION:
XS GIS Cut Line= 3
      1409755.04      6853038.01      1411763.19      6853644.04
      1413358.28      6853456.30
#Sta/Elev= 30
  2902.4 2070.85  3006.8 2067.68  3719.0 2053.53  4605.0 2049.24  4917.5 2044.56
  4981.0 2041.26  4990.6 2032.82  4991.0 2031.82  5014.2 2032.82  5022.0 2038.47
  5062.2 2043.43  5163.0 2046.16  5475.1 2055.17  5726.8 2057.99  6049.0 2067.92
  6079.2 2070.73  6122.8 2071.39  6149.7 2075.10  6190.0 2074.90  6205.8 2078.21
  6240.3 2077.13  6310.8 2084.20  6401.4 2088.67  6431.6 2093.40  6441.7 2092.48
  6471.9 2096.56  6502.1 2097.56  6548.1 2104.30  6553.1 2102.30  6606.1 2113.91
#Mann=6,-1,0
  2902.4   0.035       0  3006.8    0.07       0  4917.5    0.16       0
  4990.6    0.07       0  5014.2    0.16       0  5163.0    0.07       0
Bank Sta=4990.6,5014.2
Exp/Cntr=0.3,0.1

Type RM Length L Ch R = 1,41288,989,989,989
BEGIN DESCRIPTION:
Bitter Creek 31.0
END DESCRIPTION:
XS GIS Cut Line= 3
      1409955.00      6853388.00      1411955.05      6854578.02
      1412955.00      6854588.00
#Sta/Elev= 30
  2672.7 2065.36  3242.9 2054.42  3292.0 2055.37  3403.0 2052.98  3445.8 2054.62
  3498.5 2051.07  3664.0 2048.50  3743.8 2049.57  4057.4 2046.10  4386.5 2046.63
  4627.6 2042.60  4912.3 2042.17  4986.3 2038.22  4991.2 2029.68  4991.6 2028.68
  5014.8 2029.68  5020.0 2035.76  5060.0 2040.51  5070.0 2043.62  5089.0 2055.09
  5130.0 2054.93  5150.0 2061.71  5170.0 2063.57  5310.0 2062.03  5610.0 2075.34
  5730.0 2082.96  5770.0 2088.92  5920.0 2096.27  5950.0 2101.14  6000.0 2121.35
#Mann=4,-1,0
  2672.7    0.07       0  4991.2    0.07       0  5014.8    0.07       0
  5089.0    0.07       0
Bank Sta=4991.2,5014.8
Exp/Cntr=0.3,0.1

Type RM Length L Ch R = 1,40299,708,708,708
BEGIN DESCRIPTION:
Bitter Creek 30.0
END DESCRIPTION:
XS GIS Cut Line= 3
      1410054.97      6853887.98      1412054.84      6855503.06
      1413055.00      6854588.00
#Sta/Elev= 30
  2429.4 2059.73  3033.6 2048.67  3370.0 2046.99  3475.7 2044.42  4139.8 2042.68
  4229.4 2042.58  4260.6 2042.68  4317.3 2042.87  4519.4 2042.00  4712.2 2042.22
  4782.6 2034.00  4898.1 2033.98  4961.6 2037.17  4983.0 2027.15  4983.6 2026.15
  5014.5 2027.15  5025.1 2035.17  5145.4 2042.69  5343.3 2046.01  5428.4 2057.42
  5602.3 2056.67  5654.6 2059.15  5945.2 2077.12  6022.9 2084.14  6065.5 2092.21
  6100.6 2091.76  6182.0 2100.04  6209.0 2108.38  6299.2 2136.03  6355.6 2142.31
#Mann=15,-1,0
  2429.4    0.07       0  3370.0   0.035       0  3475.7    0.07       0
  4139.8   0.035       0  4229.4    0.07       0  4260.6   0.035       0
  4317.3    0.07       0  4519.4   0.045       0  4898.1    0.07       0
  4983.0    0.07       0  5014.5    0.07       0  5602.3   0.035       0
  5654.6    0.07       0  6182.0    0.16       0  6209.0    0.07       0
Bank Sta=4983,5014.5
Exp/Cntr=0.3,0.1

Type RM Length L Ch R = 1,39591,2247,2247,2247
BEGIN DESCRIPTION:
Bitter Creek 29.1
END DESCRIPTION:
XS GIS Cut Line= 3
      1409624.04      6855494.48      1412255.08      6856138.03
      1413779.79      6855570.25
#Sta/Elev= 30
  2291.4 2080.90  2405.6 2081.05  2452.7 2068.97  2577.6 2055.62  2673.3 2051.38
  3347.1 2041.25  3628.8 2038.66  3690.1 2032.38  3816.0 2038.56  4405.7 2040.88
  4643.4 2040.77  4898.4 2032.00  4930.7 2035.55  4940.0 2038.12  4958.7 2032.98
  4976.5 2036.15  4987.4 2025.54  4987.9 2024.54  5011.0 2025.54  5021.3 2033.22
  5125.8 2041.05  5439.9 2040.20  5651.3 2042.52  6073.5 2050.33  6214.5 2059.57
  6227.1 2064.11  6408.5 2073.02  6429.8 2077.69  6461.8 2073.58  6627.0 2084.66
#Mann=9,-1,0
  2291.4   0.035       0  3347.1   0.045       0  3690.1    0.07       0
  4405.7   0.045       0  4930.7    0.07       0  4987.4    0.07       0
  5011.0    0.07       0  5439.9   0.035       0  5651.3    0.07       0
Bank Sta=4987.4,5011
Exp/Cntr=0.3,0.1

Type RM Length L Ch R = 1,37344,999,999,999
BEGIN DESCRIPTION:
Bitter Creek 29.0
END DESCRIPTION:
XS GIS Cut Line= 3
      1410055.05      6857687.99      1411054.54      6857408.25
      1413055.04      6856187.98
#Sta/Elev= 30
  3962.1 2054.18  4057.8 2048.01  4126.0 2048.00  4138.6 2044.98  4221.7 2040.87
  4335.9 2038.76  4351.5 2031.98  4408.6 2038.74  4831.5 2038.69  4927.8 2034.56
  4978.4 2028.92  4991.6 2018.94  4991.9 2017.94  5007.4 2018.94  5008.2 2023.06
  5023.7 2026.86  5059.1 2026.14  5094.2 2031.57  5182.5 2033.85  5258.7 2030.92
  5443.8 2032.31  5479.0 2032.92  5531.0 2036.05  5788.8 2036.06  5821.8 2036.48
  6233.4 2038.23  6320.4 2038.51  6455.6 2040.98  6928.9 2041.41  7343.3 2051.41
#Mann=11,-1,0
  3962.1    0.07       0  4991.6    0.07       0  5007.4    0.07       0
  5258.7   0.035       0  5443.8    0.07       0  5479.0   0.035       0
  5788.8   0.045       0  5821.8   0.035       0  6233.4    0.07       0
  6320.4   0.035       0  6455.6    0.07       0
Bank Sta=4991.6,5007.4
Exp/Cntr=0.3,0.1

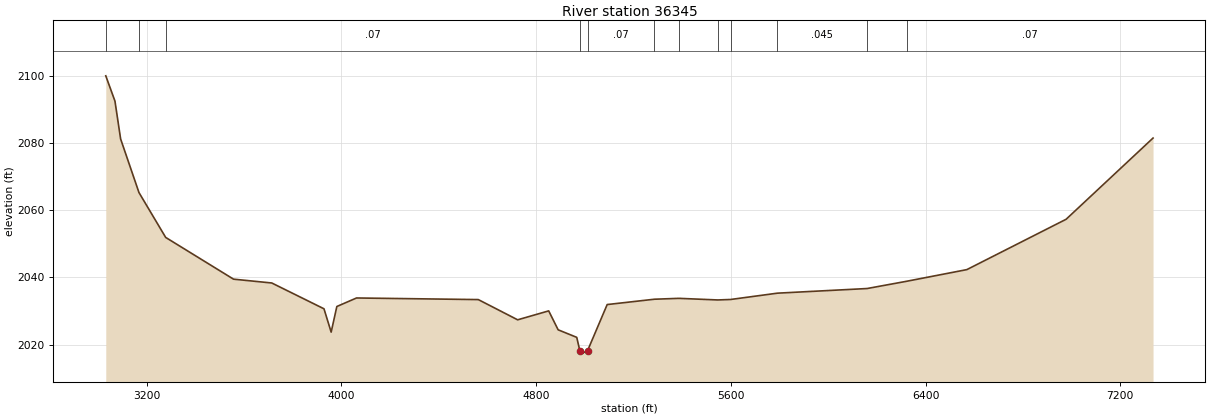
Type RM Length L Ch R = 1,36345,970,970,970
BEGIN DESCRIPTION:
Bitter Creek 28.0
END DESCRIPTION:
XS GIS Cut Line= 3
      1409954.96      6858488.02      1411755.08      6857692.92
      1413754.96      6856488.02
#Sta/Elev= 30
  3032.1 2099.98  3069.8 2092.46  3093.1 2081.19  3168.5 2065.24  3278.2 2051.89
  3556.9 2039.47  3714.1 2038.33  3928.6 2030.65  3958.1 2023.71  3981.4 2031.33
  4062.3 2033.87  4562.6 2033.39  4724.3 2027.37  4851.8 2030.03  4890.6 2024.40
  4967.1 2022.15  4979.8 2018.16  4980.4 2017.16  5011.4 2018.16  5092.1 2031.91
  5286.4 2033.50  5387.1 2033.76  5546.3 2033.28  5599.0 2033.42  5791.5 2035.30
  6159.9 2036.68  6322.5 2038.84  6569.8 2042.31  6977.6 2057.29  7334.8 2081.46
#Mann=12,-1,0
  3032.1    0.07       0  3168.5    0.16       0  3278.2    0.07       0
  4979.8    0.07       0  5011.4    0.07       0  5286.4   0.045       0
  5387.1    0.07       0  5546.3   0.045       0  5599.0    0.07       0
  5791.5   0.045       0  6159.9   0.035       0  6322.5    0.07       0
Bank Sta=4979.8,5011.4
Exp/Cntr=0.3,0.1