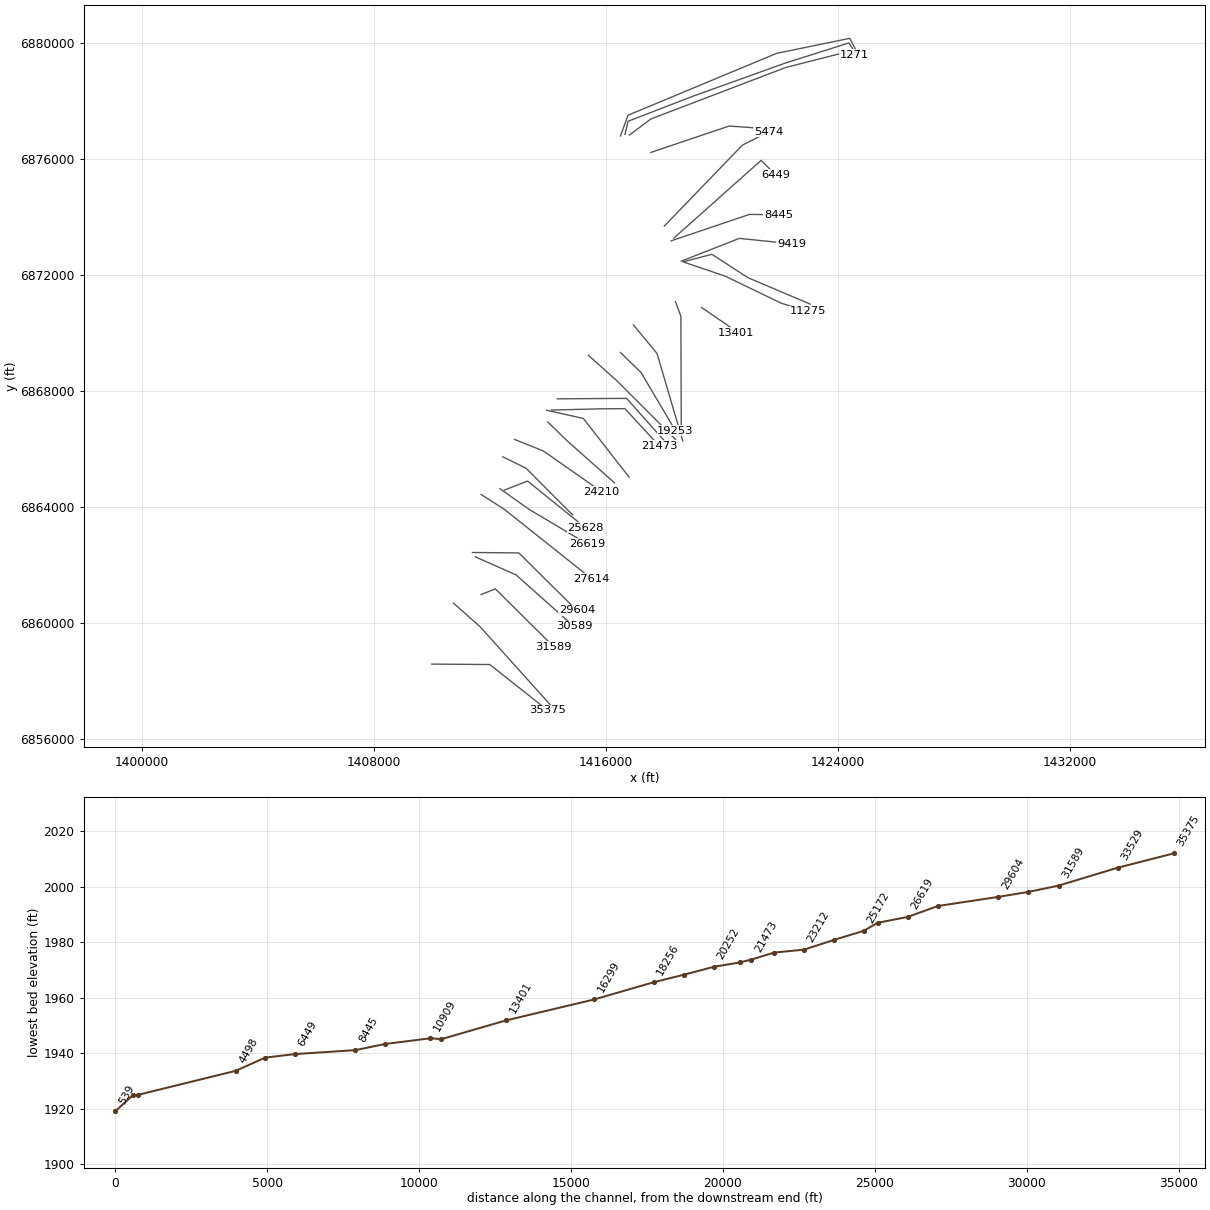
HEC-RAS study Bitter Creek.prj: Bitter Creek Base Level Engineering

--- Bitter Creek.g01 (geometry) --- (continued)

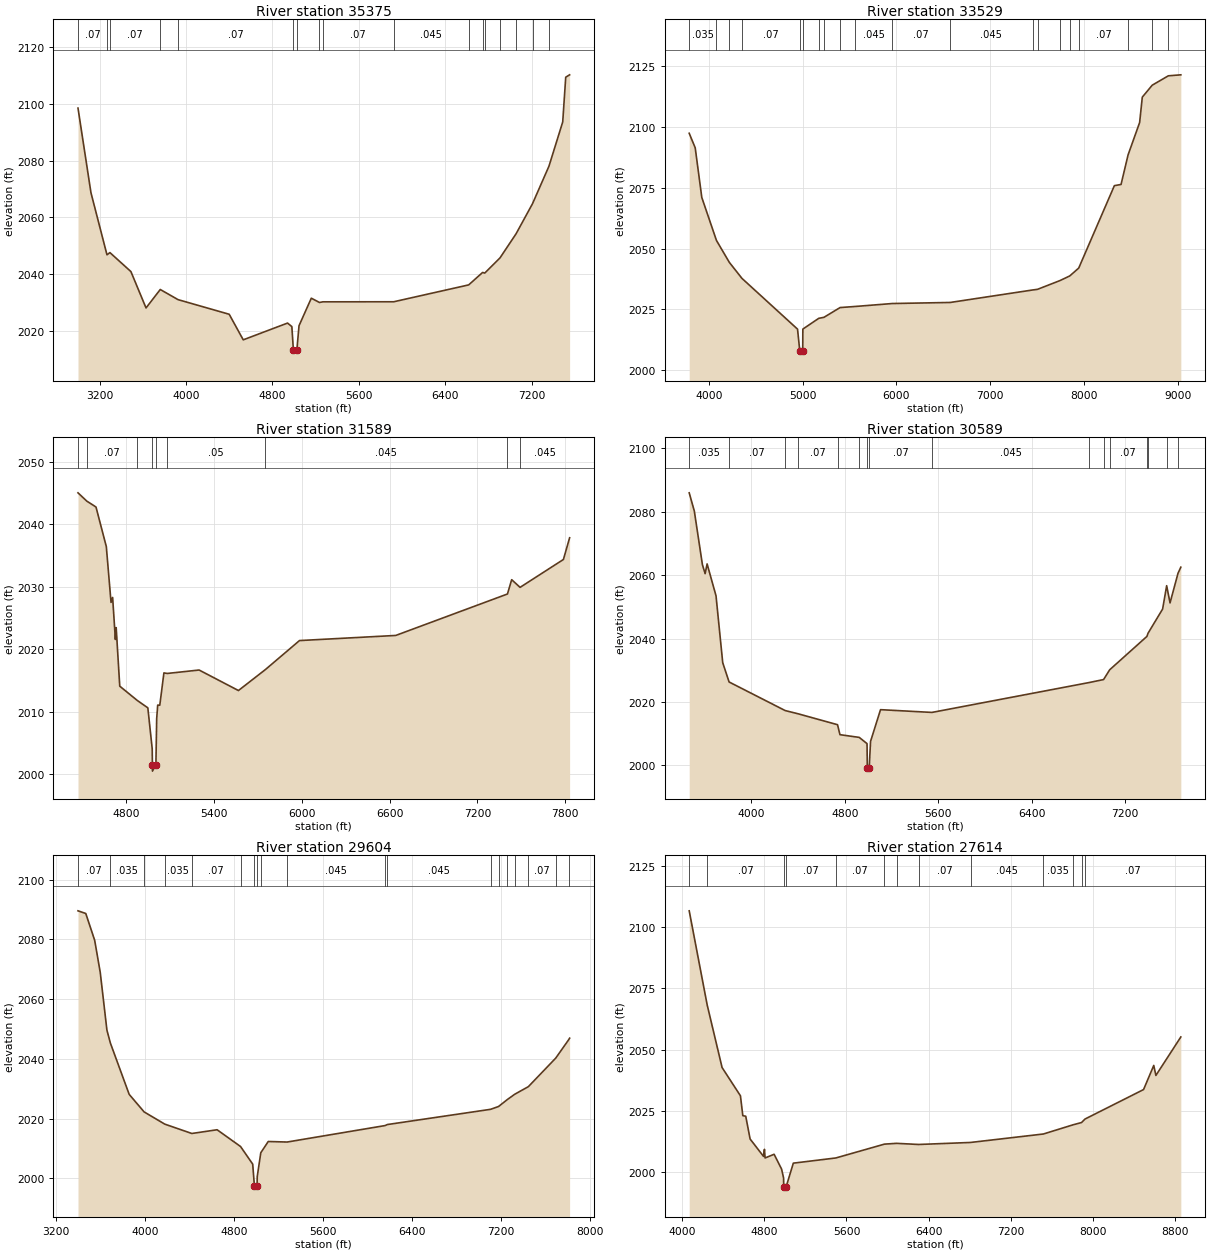
Type RM Length L Ch R = 1,35375,1846,1846,1846
BEGIN DESCRIPTION:
Bitter Creek 27.0
END DESCRIPTION:
XS GIS Cut Line= 3
      1410005.00      6858588.00      1412005.04      6858573.02
      1414005.01      6856987.99
#Sta/Elev= 30
  2999.9 2098.54  3119.9 2068.69  3268.3 2046.77  3295.6 2047.56  3489.9 2040.86
  3629.9 2028.03  3761.6 2034.54  3926.4 2030.96  4399.9 2025.80  4529.9 2016.78
  4940.0 2022.69  4980.0 2021.46  4994.3 2013.09  4994.9 2012.09  5026.1 2013.09
  5046.5 2021.77  5160.2 2031.47  5235.8 2029.96  5267.3 2030.19  5923.3 2030.21
  6617.2 2036.16  6746.5 2040.56  6766.0 2040.33  6907.3 2045.69  7056.0 2054.19
  7208.3 2064.81  7360.6 2078.04  7488.1 2093.67  7515.8 2109.44  7551.9 2110.28
#Mann=17,-1,0
  2999.9    0.07       0  3268.3    0.16       0  3295.6    0.07       0
  3761.6   0.035       0  3926.4    0.07       0  4994.3    0.07       0
  5026.1    0.07       0  5235.8   0.035       0  5267.3    0.07       0
  5923.3   0.045       0  6617.2   0.035       0  6746.5    0.07       0
  6766.0   0.035       0  6907.3    0.07       0  7056.0   0.063       0
  7208.3   0.035       0  7360.6    0.07       0
Bank Sta=4994.3,5026.1
Exp/Cntr=0.3,0.1

Type RM Length L Ch R = 1,33529,1940,1940,1940
BEGIN DESCRIPTION:
Bitter Creek 26.0
END DESCRIPTION:
XS GIS Cut Line= 3
      1410754.98      6860688.02      1411660.16      6859887.62
      1414355.03      6856887.97
#Sta/Elev= 30
  3791.7 2097.48  3855.7 2091.49  3926.0 2071.03  4082.2 2053.34  4219.6 2044.30
  4354.1 2037.71  4946.5 2016.80  4970.1 2007.92  4970.7 2006.92  5001.8 2007.92
  5003.1 2016.82  5172.1 2021.24  5228.3 2021.67  5400.2 2025.69  5561.8 2026.14
  5956.0 2027.35  6574.0 2027.79  7452.4 2032.93  7505.0 2033.20  7745.0 2036.82
  7848.4 2038.72  7944.0 2041.96  8324.1 2075.91  8395.1 2076.40  8470.1 2088.59
  8593.2 2101.90  8621.6 2112.36  8727.3 2117.29  8898.9 2121.15  9032.4 2121.56
#Mann=20,-1,0
  3791.7   0.035       0  4082.2    0.07       0  4219.6   0.035       0
  4354.1    0.07       0  4970.1    0.07       0  5001.8    0.07       0
  5172.1   0.045       0  5228.3    0.07       0  5400.2   0.045       0
  5561.8   0.045       0  5956.0    0.07       0  6574.0   0.045       0
  7452.4    0.07       0  7505.0   0.045       0  7745.0   0.035       0
  7848.4   0.035       0  7944.0    0.07       0  8470.1   0.035       0
  8727.3    0.07       0  8898.9   0.035       0
Bank Sta=4970.1,5001.8
Exp/Cntr=0.3,0.1

Type RM Length L Ch R = 1,31589,1000,1000,1000
BEGIN DESCRIPTION:
Bitter Creek 25.0
END DESCRIPTION:
XS GIS Cut Line= 3
      1411705.01      6860988.00      1412196.50      6861182.30
      1414204.98      6859188.02
#Sta/Elev= 30
  4471.5 2044.99  4531.4 2043.67  4594.5 2042.72  4665.0 2036.39  4697.3 2027.46
  4708.1 2028.26  4727.0 2021.54  4732.4 2023.43  4756.8 2014.07  4876.2 2011.79
  4948.7 2010.60  4978.5 2004.06  4979.9 2001.48  4980.3 2000.48  5003.7 2001.48
  5009.1 2008.85  5016.1 2011.04  5030.3 2011.02  5058.5 2016.19  5081.2 2016.10
  5299.0 2016.65  5567.7 2013.37  5751.7 2016.72  5984.8 2021.36  6642.5 2022.18
  7405.7 2028.81  7434.5 2031.10  7491.9 2029.87  7788.0 2034.33  7830.4 2037.80
#Mann=9,-1,0
  4471.5   0.035       0  4531.4    0.07       0  4876.2    0.05       0
  4979.9    0.07       0  5003.7    0.05       0  5081.2    0.05       0
  5751.7   0.045       0  7405.7    0.07       0  7491.9   0.045       0
Bank Sta=4979.9,5003.7
Exp/Cntr=0.3,0.1

Type RM Length L Ch R = 1,30589,985,985,985
BEGIN DESCRIPTION:
Bitter Creek 24.0
END DESCRIPTION:
XS GIS Cut Line= 3
      1411504.95      6862288.02      1412905.20      6861667.94
      1414905.00      6859888.00
#Sta/Elev= 30
  3468.6 2085.94  3512.4 2080.19  3581.6 2063.30  3604.9 2060.46  3621.8 2063.52
  3698.1 2053.48  3755.6 2032.37  3810.0 2026.30  4289.9 2017.29  4399.6 2016.28
  4738.3 2012.83  4759.2 2009.68  4924.0 2008.83  4990.9 2006.86  4993.4 1999.19
  4993.7 1998.19  5009.4 1999.19  5021.1 2007.57  5106.4 2017.57  5546.3 2016.70
  6893.6 2026.13  7015.8 2027.06  7068.1 2030.14  7386.7 2040.66  7396.4 2041.66
  7521.3 2049.30  7555.9 2056.66  7584.8 2051.23  7653.2 2060.59  7677.2 2062.49
#Mann=16,-1,0
  3468.6   0.035       0  3810.0    0.07       0  4289.9    0.16       0
  4399.6    0.07       0  4738.3    0.05       0  4924.0    0.07       0
  4993.4    0.07       0  5009.4    0.07       0  5546.3   0.045       0
  6893.6    0.07       0  7015.8   0.035       0  7068.1    0.07       0
  7386.7   0.035       0  7396.4    0.07       0  7555.9   0.035       0
  7653.2    0.07       0
Bank Sta=4993.4,5009.4
Exp/Cntr=0.3,0.1

Type RM Length L Ch R = 1,29604,1990,1990,1990
BEGIN DESCRIPTION:
Bitter Creek 23.0
END DESCRIPTION:
XS GIS Cut Line= 3
      1411405.02      6862438.00      1413005.45      6862422.81
      1415005.01      6860437.99
#Sta/Elev= 30
  3399.5 2089.55  3469.5 2088.66  3549.5 2079.68  3599.5 2068.93  3659.5 2049.61
  3690.6 2045.29  3859.5 2028.12  3993.8 2022.25  4178.9 2018.17  4422.4 2015.03
  4649.5 2016.28  4860.3 2010.67  4969.5 2004.78  4984.9 1997.41  4985.3 1996.41
  5008.8 1997.41  5010.2 2000.62  5042.2 2008.58  5109.2 2012.35  5278.6 2012.17
  6159.0 2017.68  6179.2 2018.02  7107.5 2023.12  7178.9 2024.07  7258.6 2026.41
  7323.7 2028.15  7446.8 2030.71  7692.6 2040.26  7807.6 2046.34  7817.4 2046.93
#Mann=19,-1,0
  3399.5    0.07       0  3690.6   0.035       0  3993.8    0.07       0
  4178.9   0.035       0  4422.4    0.07       0  4860.3    0.05       0
  4984.9    0.05       0  5008.8    0.05       0  5042.2    0.07       0
  5278.6   0.045       0  6159.0    0.07       0  6179.2   0.045       0
  7107.5    0.07       0  7178.9   0.045       0  7258.6    0.07       0
  7323.7   0.045       0  7446.8    0.07       0  7692.6   0.035       0
  7807.6    0.07       0
Bank Sta=4984.9,5008.8
Exp/Cntr=0.3,0.1

Type RM Length L Ch R = 1,27614,995,995,995
BEGIN DESCRIPTION:
Bitter Creek 22.0
END DESCRIPTION:
XS GIS Cut Line= 3
      1411705.01      6864437.99      1412489.73      6863938.52
      1415504.98      6861538.02
#Sta/Elev= 30
  4069.8 2106.61  4244.9 2068.20  4389.8 2042.70  4568.4 2031.18  4591.4 2023.10
  4620.1 2022.83  4662.5 2013.56  4792.9 2006.48  4802.1 2009.36  4808.0 2005.83
  4896.1 2007.33  4968.9 2001.28  4988.5 1997.61  4989.4 1994.12  4989.8 1993.12
  5013.4 1994.12  5083.1 2003.71  5497.2 2005.83  5969.7 2011.47  6087.4 2011.79
  6303.4 2011.33  6807.4 2012.15  7516.6 2015.60  7801.7 2019.30  7888.3 2020.28
  7921.1 2021.69  8491.4 2033.72  8590.7 2043.56  8611.5 2039.49  8854.1 2055.17
#Mann=13,-1,0
  4069.8   0.035       0  4244.9    0.07       0  4989.4    0.07       0
  5013.4    0.07       0  5497.2    0.07       0  5969.7   0.035       0
  6087.4    0.05       0  6303.4    0.07       0  6807.4   0.045       0
  7516.6   0.035       0  7801.7    0.07       0  7888.3   0.035       0
  7921.1    0.07       0
Bank Sta=4989.4,5013.4
Exp/Cntr=0.3,0.1

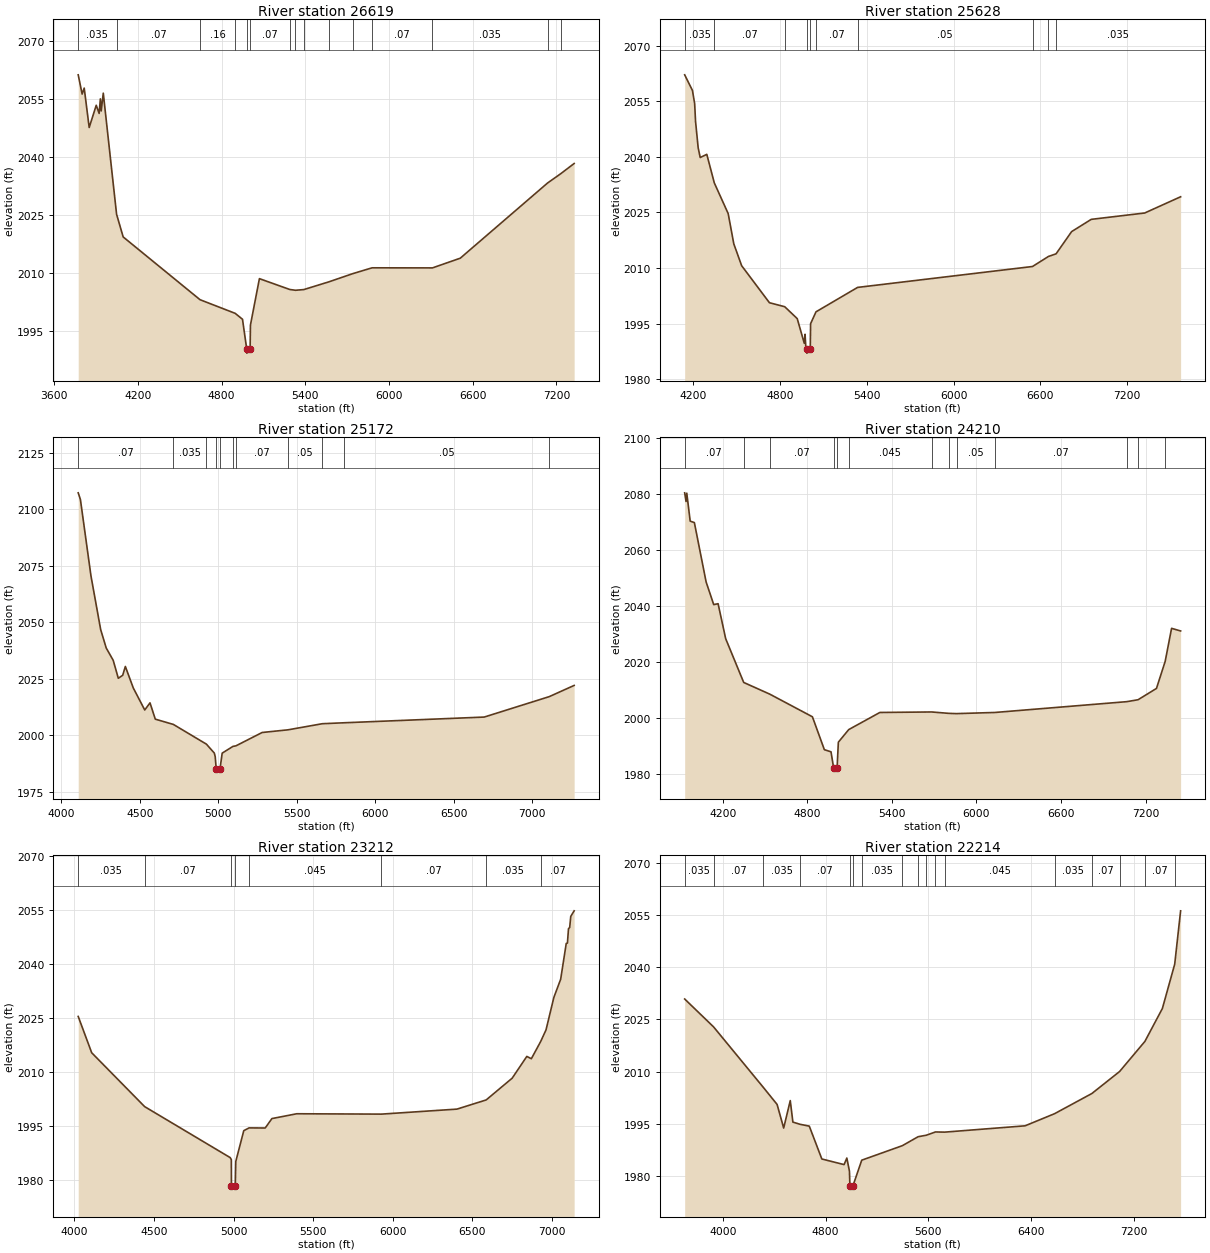
Type RM Length L Ch R = 1,26619,991,991,991
BEGIN DESCRIPTION:
Bitter Creek 21.0
END DESCRIPTION:
XS GIS Cut Line= 3
      1412355.04      6864637.97      1413355.51      6863927.79
      1415354.99      6862738.01
#Sta/Elev= 30
  3773.1 2061.18  3801.3 2056.20  3816.1 2057.75  3851.8 2047.55  3902.2 2053.30
  3923.1 2051.20  3931.8 2054.96  3937.9 2051.83  3952.7 2056.44  4048.1 2025.09
  4095.3 2019.24  4646.0 2003.00  4897.9 1999.47  4950.3 1997.94  4980.8 1990.18
  4981.3 1989.18  5004.8 1990.18  5007.3 1996.46  5071.5 2008.45  5289.4 2005.64
  5330.0 2005.44  5389.4 2005.62  5569.8 2007.63  5741.0 2009.75  5878.9 2011.25
  6311.5 2011.23  6510.7 2013.74  7136.2 2033.19  7230.3 2035.59  7326.7 2038.24
#Mann=15,-1,0
  3773.1   0.035       0  4048.1    0.07       0  4646.0    0.16       0
  4897.9    0.07       0  4980.8    0.07       0  5004.8    0.07       0
  5289.4    0.05       0  5330.0   0.035       0  5389.4    0.05       0
  5569.8    0.07       0  5741.0   0.035       0  5878.9    0.07       0
  6311.5   0.035       0  7136.2    0.07       0  7230.3   0.035       0
Bank Sta=4980.8,5004.8
Exp/Cntr=0.3,0.1

Type RM Length L Ch R = 1,25628,456,456,456
BEGIN DESCRIPTION:
Bitter Creek 20.0
END DESCRIPTION:
XS GIS Cut Line= 3
      1412505.00      6864588.00      1413305.02      6864903.01
      1415304.97      6863288.02
#Sta/Elev= 30
  4140.2 2062.13  4193.9 2057.92  4209.2 2054.37  4215.4 2049.57  4233.6 2042.43
  4247.7 2039.82  4293.2 2040.68  4345.1 2032.98  4441.1 2024.69  4480.1 2016.52
  4534.2 2010.64  4726.5 2000.65  4832.2 1999.57  4918.7 1996.36  4967.5 1989.71
  4972.9 1992.14  4978.5 1988.40  4984.8 1988.05  4985.2 1987.05  5008.8 1988.05
  5011.2 1994.99  5048.5 1998.19  5336.3 2004.78  6546.1 2010.42  6656.5 2013.13
  6709.1 2013.84  6816.6 2019.83  6952.5 2023.14  7322.0 2024.85  7570.6 2029.23
#Mann=10,-1,0
  4140.2   0.035       0  4345.1    0.07       0  4832.2    0.16       0
  4984.8    0.07       0  5008.8    0.16       0  5048.5    0.07       0
  5336.3    0.05       0  6546.1   0.035       0  6656.5    0.05       0
  6709.1   0.035       0
Bank Sta=4984.8,5008.8
Exp/Cntr=0.3,0.1

Type RM Length L Ch R = 1,25172,962,962,962
BEGIN DESCRIPTION:
Bitter Creek 19.0
END DESCRIPTION:
XS GIS Cut Line= 3
      1412455.02      6865737.99      1413254.56      6865343.18
      1414854.98      6863738.02
#Sta/Elev= 30
  4108.3 2107.19  4122.3 2104.25  4189.6 2070.44  4251.4 2046.71  4286.7 2038.60
  4331.3 2033.13  4363.6 2025.21  4391.6 2026.53  4408.5 2030.43  4459.0 2020.93
  4532.1 2011.18  4565.5 2014.34  4599.2 2007.14  4714.5 2004.80  4924.9 1996.08
  4975.2 1992.12  4980.8 1990.55  4987.2 1985.16  4987.7 1984.16  5011.3 1985.16
  5025.2 1992.11  5093.7 1995.09  5112.9 1995.34  5279.7 2001.24  5444.5 2002.42
  5663.1 2005.12  5800.0 2005.53  6694.0 2008.06  7108.5 2017.10  7266.7 2022.05
#Mann=11,-1,0
  4108.3    0.07       0  4714.5   0.035       0  4924.9    0.07       0
  4987.2    0.07       0  5011.3    0.07       0  5093.7   0.035       0
  5112.9    0.07       0  5444.5    0.05       0  5663.1    0.07       0
  5800.0    0.05       0  7108.5   0.035       0
Bank Sta=4987.2,5011.3
Exp/Cntr=0.3,0.1

Type RM Length L Ch R = 1,24210,998,998,998
BEGIN DESCRIPTION:
Bitter Creek 18.0
END DESCRIPTION:
XS GIS Cut Line= 3
      1412854.96      6866338.02      1413848.47      6865940.73
      1415854.98      6864538.02
#Sta/Elev= 30
  3930.0 2080.35  3939.5 2077.26  3944.9 2080.23  3969.1 2070.24  3998.7 2069.72
  4082.2 2048.50  4136.0 2040.43  4167.0 2040.75  4220.8 2028.27  4348.8 2012.62
  4534.0 2008.44  4836.2 2000.36  4920.9 1988.61  4968.1 1987.85  4987.1 1981.95
  4987.5 1980.95  5011.1 1981.95  5020.2 1991.29  5093.9 1995.79  5314.7 2001.90
  5681.9 2002.08  5804.3 2001.58  5858.6 2001.49  6130.8 2001.90  7066.1 2005.76
  7146.3 2006.45  7276.9 2010.49  7338.6 2020.13  7384.1 2031.95  7448.2 2031.01
#Mann=13,-1,0
  3930.0    0.07       0  4348.8   0.035       0  4534.0    0.07       0
  4987.1   0.045       0  5011.1   0.045       0  5093.9   0.045       0
  5681.9    0.05       0  5804.3   0.045       0  5858.6    0.05       0
  6130.8    0.07       0  7066.1   0.035       0  7146.3    0.07       0
  7338.6   0.035       0
Bank Sta=4987.1,5011.1
Exp/Cntr=0.3,0.1

Type RM Length L Ch R = 1,23212,998,998,998
BEGIN DESCRIPTION:
Bitter Creek 17.0
END DESCRIPTION:
XS GIS Cut Line= 3
      1414005.02      6866937.98      1414704.61      6866258.15
      1416304.97      6864838.03
#Sta/Elev= 30
  4024.5 2025.39  4109.2 2015.30  4441.6 2000.33  4979.2 1986.15  4986.3 1985.58
  4987.0 1978.39  4987.5 1977.39  5011.0 1978.39  5014.2 1985.07  5064.4 1993.64
  5097.5 1994.41  5199.0 1994.38  5241.2 1997.00  5397.2 1998.34  5929.2 1998.24
  6403.3 1999.63  6587.0 2002.18  6750.3 2008.23  6842.3 2014.28  6870.8 2013.64
  6928.7 2018.37  6962.8 2021.64  7012.1 2030.67  7054.8 2035.71  7089.9 2045.68
  7097.4 2045.79  7104.1 2049.78  7111.6 2050.12  7118.3 2053.20  7139.6 2054.75
#Mann=8,-1,0
  4024.5   0.035       0  4441.6    0.07       0  4987.0    0.07       0
  5011.0    0.07       0  5097.5   0.045       0  5929.2    0.07       0
  6587.0   0.035       0  6928.7    0.07       0
Bank Sta=4987,5011
Exp/Cntr=0.3,0.1

Type RM Length L Ch R = 1,22214,741,741,741
BEGIN DESCRIPTION:
Bitter Creek 16.0
END DESCRIPTION:
XS GIS Cut Line= 3
      1413962.51      6867344.50      1415228.13      6867061.82
      1416804.99      6865038.01
#Sta/Elev= 30
  3703.2 2030.88  3928.2 2022.88  4313.8 2005.60  4423.0 2000.62  4474.2 1993.84
  4525.5 2001.72  4546.0 1995.55  4601.7 1994.92  4673.7 1994.39  4771.4 1984.96
  4944.6 1983.35  4966.1 1985.23  4986.5 1981.45  4990.1 1977.31  4990.6 1976.31
  5014.2 1977.31  5082.2 1984.62  5399.0 1988.79  5520.5 1991.34  5585.6 1991.79
  5656.4 1992.72  5728.1 1992.67  6354.2 1994.48  6583.9 1997.96  6874.7 2003.76
  7090.4 2010.07  7287.4 2018.71  7423.6 2028.16  7519.6 2040.88  7565.6 2056.19
#Mann=17,-1,0
  3703.2   0.035       0  3928.2    0.07       0  4313.8   0.035       0
  4601.7    0.07       0  4990.1    0.07       0  5014.2    0.07       0
  5082.2   0.035       0  5399.0   0.045       0  5520.5    0.07       0
  5585.6   0.045       0  5656.4    0.07       0  5728.1   0.045       0
  6583.9   0.035       0  6874.7    0.07       0  7090.4   0.035       0
  7287.4    0.07       0  7519.6   0.035       0
Bank Sta=4990.1,5014.2
Exp/Cntr=0.3,0.1

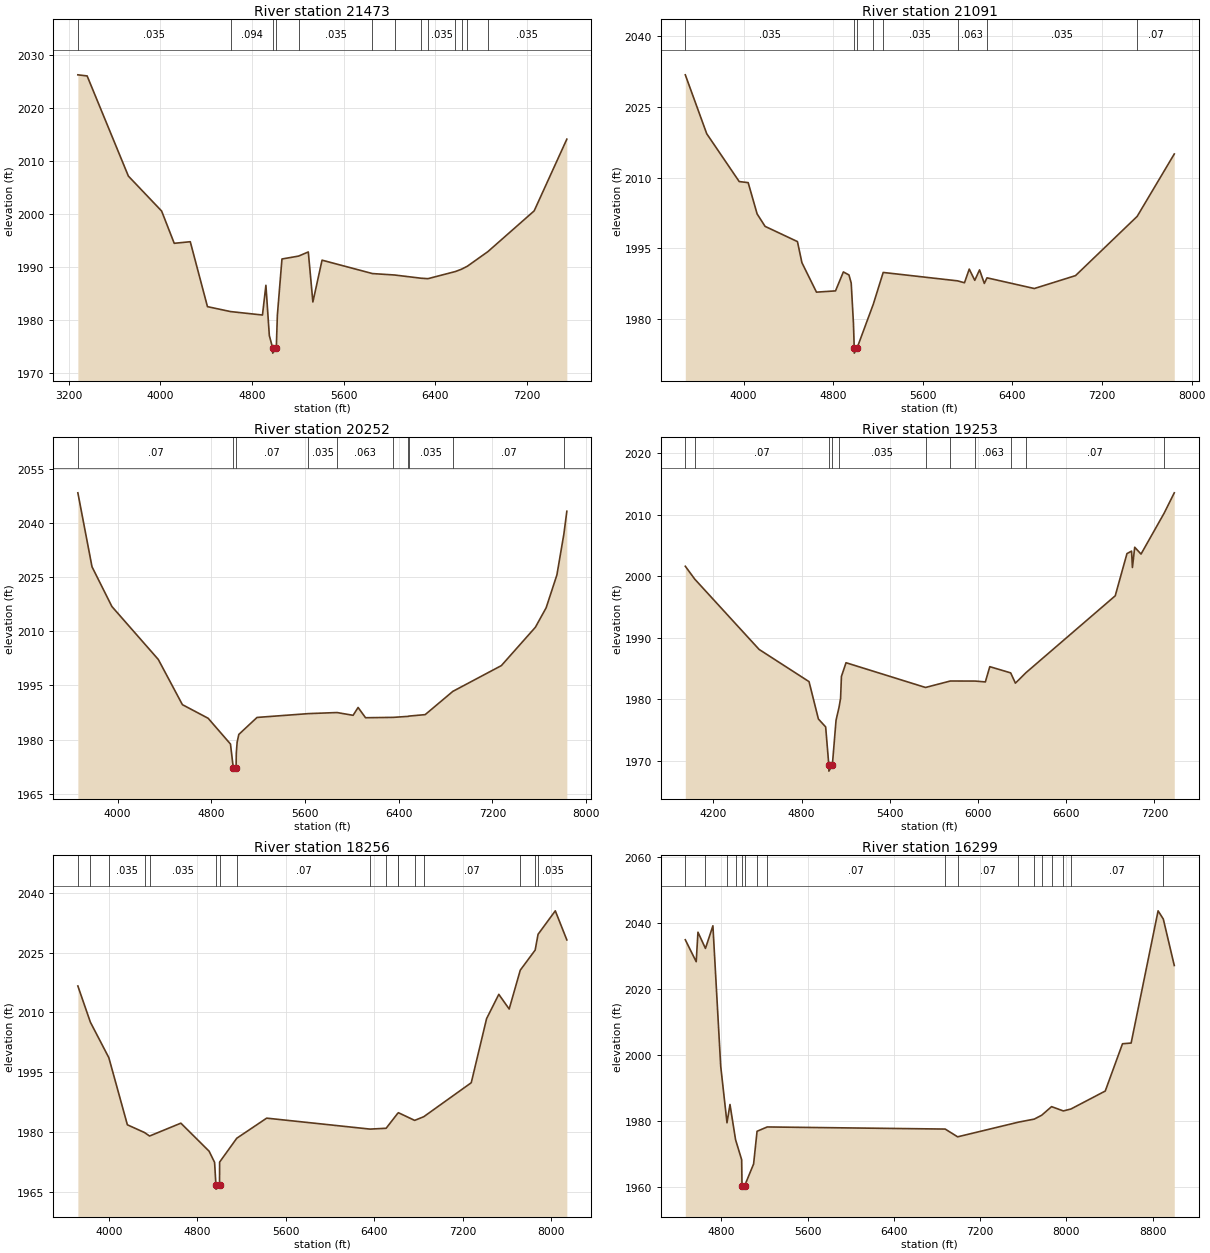
Type RM Length L Ch R = 1,21473,382,382,382
BEGIN DESCRIPTION:
Bitter Creek 4161
END DESCRIPTION:
XS GIS Cut Line= 4
      1414134.07      6867351.43      1415852.95      6867393.84
      1416661.86      6867400.04      1417838.95      6866118.79
#Sta/Elev= 30
  3280.6 2026.30  3361.6 2026.09  3721.7 2007.19  4011.8 2000.60  4121.8 1994.51
  4261.8 1994.81  4411.9 1982.56  4613.5 1981.63  4892.0 1980.98  4922.0 1986.59
  4952.0 1977.10  4980.8 1974.79  4981.4 1973.79  5012.8 1974.79  5022.1 1980.96
  5062.1 1991.55  5207.4 1992.10  5292.1 1992.88  5332.1 1983.44  5412.1 1991.33
  5852.2 1988.80  6044.9 1988.53  6278.5 1987.92  6337.0 1987.84  6576.7 1989.19
  6630.2 1989.63  6680.6 1990.19  6860.2 1992.95  7263.7 2000.63  7548.8 2014.16
#Mann=13,-1,0
  3280.6   0.035       0  4613.5   0.094       0  4980.8    0.07       0
  5012.8   0.094       0  5207.4   0.035       0  5852.2    0.07       0
  6044.9   0.035       0  6278.5    0.07       0  6337.0   0.035       0
  6576.7    0.07       0  6630.2   0.035       0  6680.6    0.07       0
  6860.2   0.035       0
Bank Sta=4980.8,5012.8
Exp/Cntr=0.3,0.1

Type RM Length L Ch R = 1,21091,839,839,839
BEGIN DESCRIPTION:
Bitter Creek 15.0
END DESCRIPTION:
XS GIS Cut Line= 4
      1414333.73      6867738.58      1415854.80      6867748.07
      1416719.23      6867753.55      1418036.88      6866275.03
#Sta/Elev= 30
  3478.9 2031.82  3670.2 2019.32  3960.2 2009.17  4040.2 2008.94  4120.2 2002.30
  4191.3 1999.66  4480.2 1996.43  4520.2 1991.95  4650.2 1985.70  4820.2 1985.97
  4890.2 1989.99  4940.2 1989.35  4960.2 1987.63  4980.2 1979.12  4987.3 1973.76
  4987.7 1972.76  5011.3 1973.76  5157.4 1983.14  5245.8 1989.88  5909.4 1988.10
  5971.6 1987.69  6014.2 1990.59  6063.5 1988.21  6106.2 1990.43  6148.8 1987.55
  6172.8 1988.74  6595.2 1986.47  6963.2 1989.21  7513.5 2001.78  7844.9 2015.02
#Mann=8,-1,0
  3478.9   0.035       0  4987.3   0.035       0  5011.3   0.035       0
  5157.4   0.094       0  5245.8   0.035       0  5909.4   0.063       0
  6172.8   0.035       0  7513.5    0.07       0
Bank Sta=4987.3,5011.3
Exp/Cntr=0.3,0.1

Type RM Length L Ch R = 1,20252,999,999,999
BEGIN DESCRIPTION:
Bitter Creek 14.0
END DESCRIPTION:
XS GIS Cut Line= 3
      1415404.99      6869238.01      1416402.27      6868344.51
      1418405.03      6866337.97
#Sta/Elev= 30
  3661.0 2048.47  3781.8 2027.94  3951.5 2016.92  4347.7 2002.22  4553.3 1989.68
  4773.1 1985.90  4963.7 1978.75  4987.5 1972.23  4987.9 1971.23  5011.6 1972.23
  5013.6 1976.36  5020.7 1979.27  5034.8 1981.41  5190.4 1986.13  5628.2 1987.19
  5873.3 1987.49  6010.6 1986.72  6053.1 1988.90  6116.7 1986.05  6353.4 1986.15
  6482.0 1986.43  6486.4 1986.50  6625.8 1986.91  6862.2 1993.37  7276.3 2000.52
  7566.3 2011.15  7658.2 2016.55  7750.1 2025.67  7809.8 2037.04  7835.0 2043.35
#Mann=10,-1,0
  3661.0    0.07       0  4987.5    0.07       0  5011.6    0.07       0
  5628.2   0.035       0  5873.3   0.063       0  6353.4   0.035       0
  6482.0   0.063       0  6486.4   0.035       0  6862.2    0.07       0
  7809.8   0.035       0
Bank Sta=4987.5,5011.6
Exp/Cntr=0.3,0.1

Type RM Length L Ch R = 1,19253,997,997,997
BEGIN DESCRIPTION:
Bitter Creek 13.0
END DESCRIPTION:
XS GIS Cut Line= 3
      1416504.98      6869338.02      1417215.63      6868648.05
      1418405.01      6866637.98
#Sta/Elev= 30
  4009.5 2001.62  4073.8 1999.53  4511.5 1988.11  4851.1 1982.88  4914.8 1976.81
  4964.2 1975.52  4985.7 1969.34  4986.2 1968.34  5009.8 1969.34  5034.9 1976.61
  5055.2 1978.71  5065.7 1980.14  5071.5 1983.73  5102.8 1985.95  5643.5 1981.93
  5812.4 1982.98  5981.8 1982.97  6050.5 1982.83  6080.7 1985.31  6222.8 1984.30
  6255.0 1982.63  6326.6 1984.33  6933.9 1996.82  7013.8 2003.68  7045.1 2004.08
  7050.9 2001.42  7066.5 2004.71  7109.4 2003.60  7267.0 2010.26  7335.6 2013.55
#Mann=11,-1,0
  4009.5   0.035       0  4073.8    0.07       0  4985.7    0.07       0
  5009.8    0.07       0  5055.2   0.035       0  5643.5    0.07       0
  5812.4   0.035       0  5981.8   0.063       0  6222.8   0.035       0
  6326.6    0.07       0  7267.0   0.035       0
Bank Sta=4985.7,5009.8
Exp/Cntr=0.3,0.1

Type RM Length L Ch R = 1,18256,1957,1957,1957
BEGIN DESCRIPTION:
Bitter Creek 12.0
END DESCRIPTION:
XS GIS Cut Line= 3
      1416955.01      6870287.99      1417768.58      6869301.23
      1418655.00      6866288.01
#Sta/Elev= 30
  3721.1 2016.62  3834.3 2007.53  4001.1 1998.62  4168.7 1981.77  4324.1 1979.82
  4369.3 1978.95  4652.1 1982.18  4907.5 1975.14  4957.0 1972.33  4969.2 1966.62
  4969.8 1965.62  5001.4 1966.62  5002.5 1972.41  5157.6 1978.40  5427.9 1983.44
  6362.3 1980.69  6507.5 1980.90  6610.6 1984.59  6618.9 1984.80  6765.5 1982.88
  6847.6 1983.80  7276.9 1992.33  7415.5 2008.42  7526.0 2014.52  7619.7 2010.84
  7720.0 2020.59  7854.6 2025.63  7880.8 2029.59  8036.7 2035.49  8140.9 2028.19
#Mann=17,-1,0
  3721.1   0.035       0  3834.3    0.07       0  4001.1   0.035       0
  4324.1    0.07       0  4369.3   0.035       0  4969.2   0.035       0
  5001.4   0.035       0  5157.6    0.07       0  6362.3   0.035       0
  6507.5   0.063       0  6610.6   0.094       0  6618.9   0.063       0
  6765.5   0.035       0  6847.6    0.07       0  7720.0   0.035       0
  7854.6    0.07       0  7880.8   0.035       0
Bank Sta=4969.2,5001.4
Exp/Cntr=0.3,0.1

Type RM Length L Ch R = 1,16299,2898,2898,2898
BEGIN DESCRIPTION:
Bitter Creek 11.0
END DESCRIPTION:
XS GIS Cut Line= 3
      1418404.99      6871088.03      1418589.94      6870588.15
      1418605.00      6866587.98
#Sta/Elev= 30
  4467.0 2034.89  4568.1 2028.25  4584.3 2037.18  4653.8 2032.27  4722.9 2039.12
  4795.3 1996.60  4853.5 1979.50  4881.2 1985.03  4932.9 1974.38  4989.5 1968.30
  4992.7 1960.41  4993.1 1959.41  5016.8 1960.41  5100.2 1967.03  5132.2 1976.92
  5226.7 1978.23  6876.4 1977.59  6991.8 1975.24  7555.2 1979.68  7702.4 1980.61
  7771.0 1981.78  7862.7 1984.38  7971.4 1983.08  8041.9 1983.66  8360.2 1989.10
  8520.2 2003.41  8600.2 2003.63  8850.2 2043.65  8898.5 2041.16  9000.2 2027.11
#Mann=17,-1,0
  4467.0    0.07       0  4653.8   0.035       0  4853.5    0.16       0
  4932.9    0.07       0  4992.7    0.07       0  5016.8    0.07       0
  5132.2   0.035       0  5226.7    0.07       0  6876.4   0.035       0
  6991.8    0.07       0  7555.2   0.035       0  7702.4   0.063       0
  7771.0   0.094       0  7862.7   0.063       0  7971.4   0.035       0
  8041.9    0.07       0  8898.5   0.035       0
Bank Sta=4992.7,5016.8
Exp/Cntr=0.3,0.1

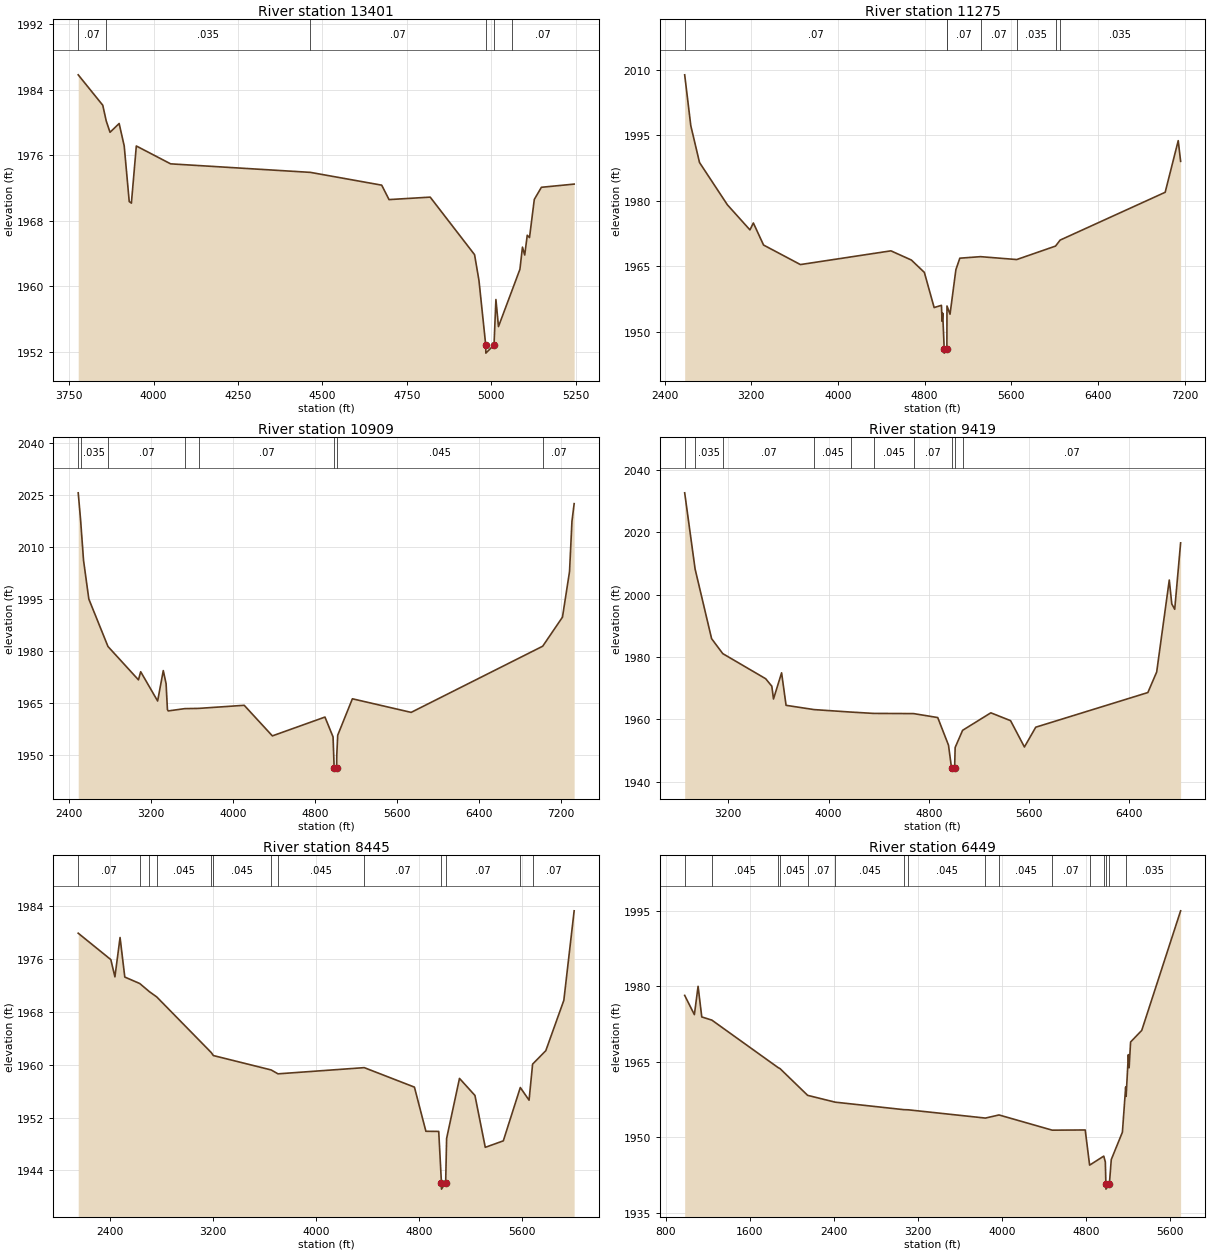
Type RM Length L Ch R = 1,13401,2126,2126,2126
BEGIN DESCRIPTION:
Bitter Creek 10.0
END DESCRIPTION:
XS GIS Cut Line= 3
      1419304.96      6870888.02      1420314.87      6870198.05
      1420478.21      6870014.64
#Sta/Elev= 30
  3776.9 1985.82  3849.6 1982.11  3859.9 1980.19  3871.1 1978.81  3898.1 1979.88
  3913.1 1977.15  3928.0 1970.36  3934.4 1970.17  3949.0 1977.14  4050.6 1974.96
  4464.5 1973.92  4675.7 1972.36  4697.4 1970.60  4819.3 1970.90  4950.7 1963.88
  4963.8 1960.71  4983.7 1952.87  4984.1 1951.87  5008.3 1952.87  5013.9 1958.41
  5021.5 1955.11  5061.9 1959.55  5085.0 1962.10  5092.5 1964.80  5099.2 1963.84
  5106.7 1966.25  5113.4 1965.97  5127.6 1970.62  5148.6 1972.10  5245.6 1972.49
#Mann=6,-1,0
  3776.9    0.07       0  3859.9   0.035       0  4464.5    0.07       0
  4983.7    0.07       0  5008.3    0.07       0  5061.9    0.07       0
Bank Sta=4983.7,5008.3
Exp/Cntr=0.3,0.1

Type RM Length L Ch R = 1,11275,366,366,366
BEGIN DESCRIPTION:
Bitter Creek 9.0
END DESCRIPTION:
XS GIS Cut Line= 4
      1418711.52      6872447.41      1420123.00      6871968.24
      1422050.95      6871037.03      1422956.06      6870761.41
#Sta/Elev= 30
  2585.5 2008.79  2642.0 1997.16  2722.4 1988.73  2979.9 1979.05  3188.1 1973.31
  3219.4 1974.90  3313.6 1969.85  3653.7 1965.38  4489.2 1968.52  4678.0 1966.42
  4797.8 1963.59  4888.2 1955.55  4955.6 1956.05  4961.5 1952.41  4967.1 1954.27
  4981.0 1946.12  4981.4 1945.12  5005.8 1946.12  5005.9 1947.21  5006.7 1955.90
  5034.9 1954.03  5088.9 1964.21  5125.3 1966.84  5316.6 1967.19  5650.6 1966.53
  6008.8 1969.61  6051.2 1970.98  7020.8 1981.92  7141.3 1993.73  7163.3 1989.00
#Mann=7,-1,0
  2585.5    0.07       0  5005.8    0.07       0  5005.9    0.07       0
  5316.6    0.07       0  5650.6   0.035       0  6008.8    0.07       0
  6051.2   0.035       0
Bank Sta=4981,5005.8
Exp/Cntr=0.3,0.1

Type RM Length L Ch R = 1,10909,1490,1490,1490
BEGIN DESCRIPTION:
Bitter Creek 8.0
END DESCRIPTION:
XS GIS Cut Line= 4
      1418664.67      6872463.03      1419659.46      6872723.44
      1420905.01      6871916.15      1423050.01      6871004.73
#Sta/Elev= 30
  2487.4 2025.67  2510.7 2017.85  2539.4 2006.20  2591.1 1995.04  2778.1 1981.36
  3075.7 1971.74  3097.6 1974.08  3263.0 1965.64  3318.2 1974.41  3345.7 1970.62
  3358.6 1963.19  3366.4 1962.78  3528.5 1963.44  3663.9 1963.51  4108.5 1964.40
  4383.5 1955.58  4897.1 1961.01  4976.2 1955.28  4986.7 1946.42  4987.2 1945.42
  5011.5 1946.42  5012.2 1949.82  5021.7 1955.78  5164.9 1966.28  5738.8 1962.36
  7023.5 1981.44  7216.5 1989.82  7285.5 2002.96  7309.2 2017.48  7330.6 2022.55
#Mann=8,-1,0
  2487.4    0.07       0  2510.7   0.035       0  2778.1    0.07       0
  3528.5   0.045       0  3663.9    0.07       0  4986.7    0.07       0
  5011.5   0.045       0  7023.5    0.07       0
Bank Sta=4986.7,5011.5
Exp/Cntr=0.3,0.1

Type RM Length L Ch R = 1,9419,974,974,974
BEGIN DESCRIPTION:
Bitter Creek 7.0
END DESCRIPTION:
XS GIS Cut Line= 3
      1418605.04      6872488.01      1420605.00      6873273.00
      1422405.02      6873088.00
#Sta/Elev= 30
  2851.5 2032.61  2934.7 2008.17  3066.3 1985.85  3155.3 1981.05  3498.0 1972.99
  3546.9 1970.59  3560.5 1966.50  3624.9 1974.89  3660.7 1964.46  3884.8 1963.09
  4177.1 1962.30  4358.5 1961.87  4678.4 1961.81  4871.1 1960.54  4957.0 1951.69
  4981.2 1944.36  4981.6 1943.36  5005.9 1944.36  5010.1 1950.94  5069.7 1956.45
  5295.0 1962.06  5452.4 1959.54  5562.9 1951.10  5653.4 1957.45  6548.1 1968.56
  6618.5 1975.15  6719.0 2004.64  6739.1 1996.96  6762.4 1995.26  6809.5 2016.56
#Mann=10,-1,0
  2851.5    0.07       0  2934.7   0.035       0  3155.3    0.07       0
  3884.8   0.045       0  4177.1    0.07       0  4358.5   0.045       0
  4678.4    0.07       0  4981.2   0.045       0  5005.9    0.07       0
  5069.7    0.07       0
Bank Sta=4981.2,5005.9
Exp/Cntr=0.3,0.1

Type RM Length L Ch R = 1,8445,1996,1996,1996
BEGIN DESCRIPTION:
Bitter Creek 6.0
END DESCRIPTION:
XS GIS Cut Line= 3
      1418255.04      6873188.01      1420952.97      6874099.99
      1421955.00      6874088.00
#Sta/Elev= 30
  2152.1 1979.92  2405.4 1975.92  2437.1 1973.31  2477.0 1979.27  2513.7 1973.28
  2629.9 1972.30  2705.1 1971.06  2761.7 1970.27  3184.6 1961.85  3201.4 1961.39
  3650.2 1959.21  3703.1 1958.62  4372.4 1959.56  4762.1 1956.61  4851.2 1949.92
  4950.8 1949.90  4971.7 1942.16  4972.3 1941.16  5004.7 1942.16  5012.0 1948.83
  5112.0 1957.93  5232.0 1955.35  5312.1 1947.49  5452.1 1948.47  5584.1 1956.55
  5652.1 1954.63  5679.5 1960.09  5782.1 1962.13  5922.1 1969.76  6002.1 1983.31
#Mann=13,-1,0
  2152.1    0.07       0  2629.9   0.045       0  2705.1    0.07       0
  2761.7   0.045       0  3184.6    0.07       0  3201.4   0.045       0
  3650.2    0.07       0  3703.1   0.045       0  4372.4    0.07       0
  4971.7    0.07       0  5004.7    0.07       0  5584.1    0.16       0
  5679.5    0.07       0
Bank Sta=4971.7,5004.7
Exp/Cntr=0.3,0.1

Type RM Length L Ch R = 1,6449,975,975,975
BEGIN DESCRIPTION:
Bitter Creek 5.0
END DESCRIPTION:
XS GIS Cut Line= 3
      1418355.02      6873288.02      1421355.02      6875963.01
      1421852.25      6875472.29
#Sta/Elev= 30
   980.6 1978.16  1072.9 1974.34  1108.1 1979.96  1143.2 1973.88  1239.3 1973.25
  1868.1 1963.85  1887.6 1963.63  2150.5 1958.32  2412.2 1956.97  3065.5 1955.48
  3107.2 1955.45  3841.6 1953.81  3971.0 1954.43  4477.3 1951.41  4791.0 1951.45
  4832.9 1944.47  4967.4 1946.26  4982.4 1945.10  4987.7 1940.71  4988.3 1939.71
  5020.8 1940.71  5038.9 1945.58  5144.9 1951.01  5175.9 1959.99  5180.3 1958.12
  5201.5 1966.40  5208.6 1963.79  5222.8 1968.91  5328.8 1971.21  5698.6 1994.94
#Mann=16,-1,0
   980.6    0.07       0  1239.3   0.045       0  1868.1    0.07       0
  1887.6   0.045       0  2150.5    0.07       0  2412.2   0.045       0
  3065.5    0.07       0  3107.2   0.045       0  3841.6    0.07       0
  3971.0   0.045       0  4477.3    0.07       0  4832.9    0.16       0
  4967.4    0.07       0  4987.7    0.07       0  5020.8    0.07       0
  5175.9   0.035       0
Bank Sta=4987.7,5020.8
Exp/Cntr=0.3,0.1

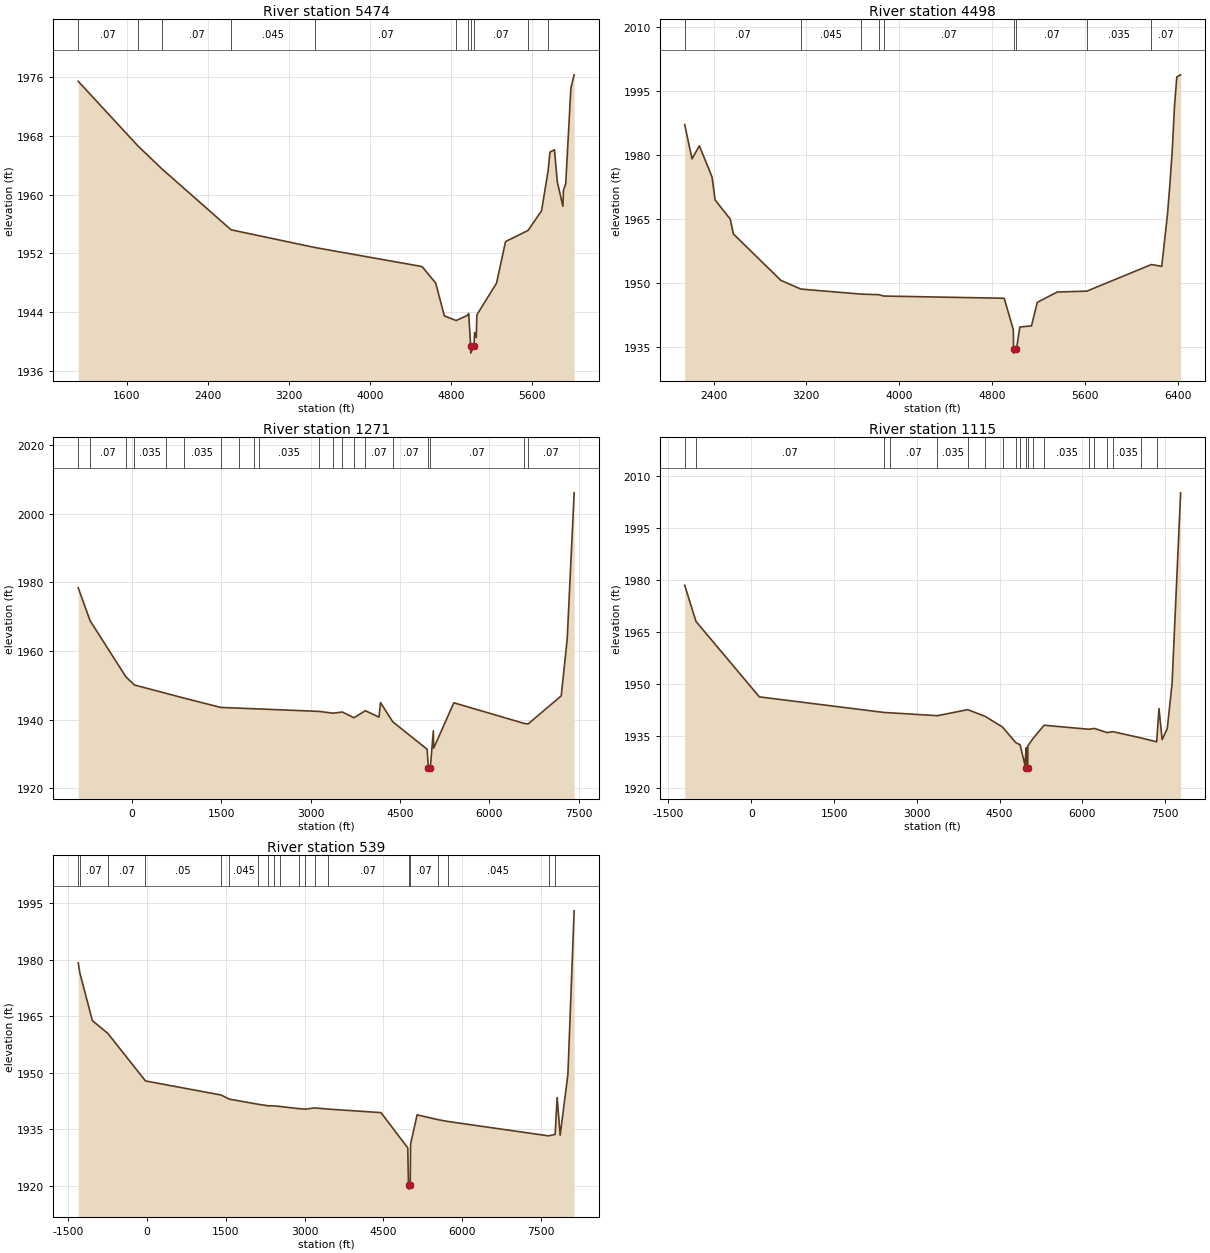
Type RM Length L Ch R = 1,5474,976,976,976
BEGIN DESCRIPTION:
Bitter Creek 4.0
END DESCRIPTION:
XS GIS Cut Line= 3
      1418018.92      6873697.68      1420709.97      6876487.94
      1421613.79      6876950.93
#Sta/Elev= 30
  1123.5 1975.41  1712.9 1966.62  1947.2 1963.53  2631.3 1955.22  3454.9 1952.82
  4515.5 1950.22  4650.1 1947.97  4735.0 1943.52  4851.3 1942.88  4965.0 1943.60
  4975.2 1943.84  4994.6 1939.45  4995.2 1938.45  5027.7 1939.45  5033.4 1941.24
  5050.0 1940.58  5055.6 1943.65  5249.8 1947.96  5338.6 1953.62  5560.7 1955.13
  5693.8 1957.80  5759.1 1963.28  5777.0 1965.79  5821.4 1966.10  5849.3 1961.75
  5904.5 1958.42  5910.3 1960.64  5932.5 1961.48  5983.2 1974.47  6015.5 1976.29
#Mann=11,-1,0
  1123.5    0.07       0  1712.9   0.045       0  1947.2    0.07       0
  2631.3   0.045       0  3454.9    0.07       0  4851.3   0.035       0
  4965.0    0.07       0  4994.6    0.07       0  5027.7    0.07       0
  5560.7   0.035       0  5759.1    0.07       0
Bank Sta=4994.6,5027.7
Exp/Cntr=0.3,0.1

Type RM Length L Ch R = 1,4498,3227,3227,3227
BEGIN DESCRIPTION:
Bitter Creek 0.1
END DESCRIPTION:
XS GIS Cut Line= 3
      1417555.00      6876238.00      1420254.49      6877148.16
      1421677.60      6877048.42
#Sta/Elev= 30
  2151.2 1987.09  2214.5 1979.09  2277.8 1982.12  2387.3 1974.83  2413.5 1969.48
  2544.7 1964.95  2570.9 1961.53  2980.1 1950.68  3153.0 1948.64  3671.5 1947.46
  3824.0 1947.33  3868.0 1947.01  4905.6 1946.49  4984.3 1939.17  4986.9 1934.67
  4987.3 1933.67  5011.7 1934.67  5040.6 1939.78  5140.9 1940.04  5191.0 1945.54
  5363.2 1947.95  5618.2 1948.16  6175.3 1954.38  6263.6 1953.94  6313.7 1966.19
  6333.8 1973.02  6353.8 1980.67  6373.9 1991.45  6393.9 1998.23  6426.6 1998.71
#Mann=9,-1,0
  2151.2    0.07       0  3153.0   0.045       0  3671.5    0.07       0
  3824.0   0.045       0  3868.0    0.07       0  4986.9    0.07       0
  5011.7    0.07       0  5618.2   0.035       0  6175.3    0.07       0
Bank Sta=4986.9,5011.7
Exp/Cntr=0.3,0.1

Type RM Length L Ch R = 1,1271,156,156,156
BEGIN DESCRIPTION:
Bitter Creek 4269
END DESCRIPTION:
XS GIS Cut Line= 5
      1416817.55      6876838.90      1417556.34      6877391.94
      1422204.50      6879167.79      1424152.60      6879664.41
      1424560.29      6879612.36
#Sta/Elev= 30
  -898.7 1978.40  -698.6 1968.77   -96.9 1952.41    45.1 1950.07   576.2 1947.63
   868.2 1946.29  1491.9 1943.54  1806.4 1943.32  2054.7 1943.15  2139.5 1943.09
  3138.8 1942.38  3379.0 1941.86  3533.1 1942.19  3728.1 1940.53  3919.0 1942.58
  4147.7 1940.71  4172.5 1944.95  4377.5 1939.36  4955.5 1931.34  4975.1 1925.98
  4975.7 1924.98  5008.2 1925.98  5059.4 1936.74  5064.6 1931.66  5403.0 1944.89
  6576.5 1938.91  6648.7 1938.72  7204.4 1946.90  7305.2 1963.53  7421.4 2006.05
#Mann=20,-1,0
  -898.7   0.035       0  -698.6    0.07       0   -96.9    0.07       0
    45.1   0.035       0   576.2   0.035       0   868.2   0.035       0
  1491.9   0.035       0  1806.4   0.035       0  2054.7    0.07       0
  2139.5   0.035       0  3138.8    0.07       0  3379.0   0.035       0
  3533.1    0.07       0  3728.1   0.063       0  3919.0    0.07       0
  4377.5    0.07       0  4975.1    0.07       0  5008.2    0.07       0
  6576.5   0.035       0  6648.7    0.07       0
Bank Sta=4975.1,5008.2
Exp/Cntr=0.3,0.1

Type RM Length L Ch R = 1,1115,576,576,576
BEGIN DESCRIPTION:
Bitter Creek 4525
END DESCRIPTION:
XS GIS Cut Line= 6
      1416666.03      6876861.55      1416770.18      6877312.89
      1419018.45      6878180.95      1422154.41      6879308.05
      1424377.82      6880013.85      1424627.83      6879645.78
#Sta/Elev= 30
 -1205.6 1978.46 -1000.0 1968.02   146.7 1946.29  2413.5 1941.78  2518.1 1941.69
  3370.9 1940.86  3921.9 1942.60  4234.2 1940.70  4552.3 1937.60  4792.5 1933.09
  4870.4 1932.49  4959.2 1926.62  4979.4 1931.61  4984.6 1925.88  4985.0 1924.88
  5009.5 1925.88  5010.8 1932.19  5103.8 1934.25  5305.0 1938.11  6115.5 1936.95
  6218.3 1937.18  6447.1 1935.99  6551.2 1936.26  7064.8 1934.44  7344.8 1933.34
  7387.1 1942.91  7444.0 1933.96  7536.8 1937.14  7623.6 1950.04  7778.7 2005.11
#Mann=20,-1,0
 -1205.6   0.035       0 -1000.0    0.07       0  2413.5   0.035       0
  2518.1    0.07       0  3370.9   0.035       0  3921.9   0.035       0
  4234.2   0.035       0  4552.3   0.035       0  4792.5    0.07       0
  4870.4   0.035       0  4984.6   0.035       0  5009.5   0.035       0
  5103.8    0.07       0  5305.0   0.035       0  6115.5    0.07       0
  6218.3   0.035       0  6447.1    0.07       0  6551.2   0.035       0
  7064.8    0.07       0  7344.8    0.07       0
Bank Sta=4984.6,5009.5
Exp/Cntr=0.3,0.1

Type RM Length L Ch R = 1,539,0,0,0
BEGIN DESCRIPTION:
Bitter Creek 4526
END DESCRIPTION:
XS GIS Cut Line= 5
      1416509.76      6876805.50      1416766.71      6877520.79
      1421888.49      6879655.04      1424412.54      6880173.57
      1424666.90      6879681.82
#Sta/Elev= 30
 -1308.7 1979.22 -1275.0 1976.39 -1038.4 1963.86  -744.4 1960.47   -28.3 1947.85
  1410.0 1944.11  1567.1 1943.02  2119.2 1941.64  2306.6 1941.25  2412.6 1941.22
  2530.8 1941.07  2898.8 1940.47  3007.7 1940.35  3190.8 1940.68  3436.6 1940.38
  4454.5 1939.43  4963.5 1930.06  4977.6 1920.11  4978.2 1919.11  5010.7 1920.11
  5016.9 1931.08  5141.7 1938.84  5536.8 1937.57  5720.5 1937.09  7643.2 1933.26
  7768.3 1933.64  7806.6 1943.45  7864.5 1933.45  8011.5 1949.60  8130.4 1993.03
#Mann=20,-1,0
 -1308.7   0.035       0 -1275.0    0.07       0  -744.4    0.07       0
   -28.3    0.05       0  1410.0    0.07       0  1567.1   0.045       0
  2119.2    0.07       0  2306.6   0.045       0  2412.6   0.035       0
  2530.8    0.07       0  2898.8   0.045       0  3007.7    0.07       0
  3190.8   0.035       0  3436.6    0.07       0  4977.6    0.07       0
  5010.7    0.07       0  5536.8   0.035       0  5720.5   0.045       0
  7643.2   0.035       0  7768.3    0.07       0
Bank Sta=4977.6,5010.7
Exp/Cntr=0.3,0.1

Chan Stop Cuts=-1