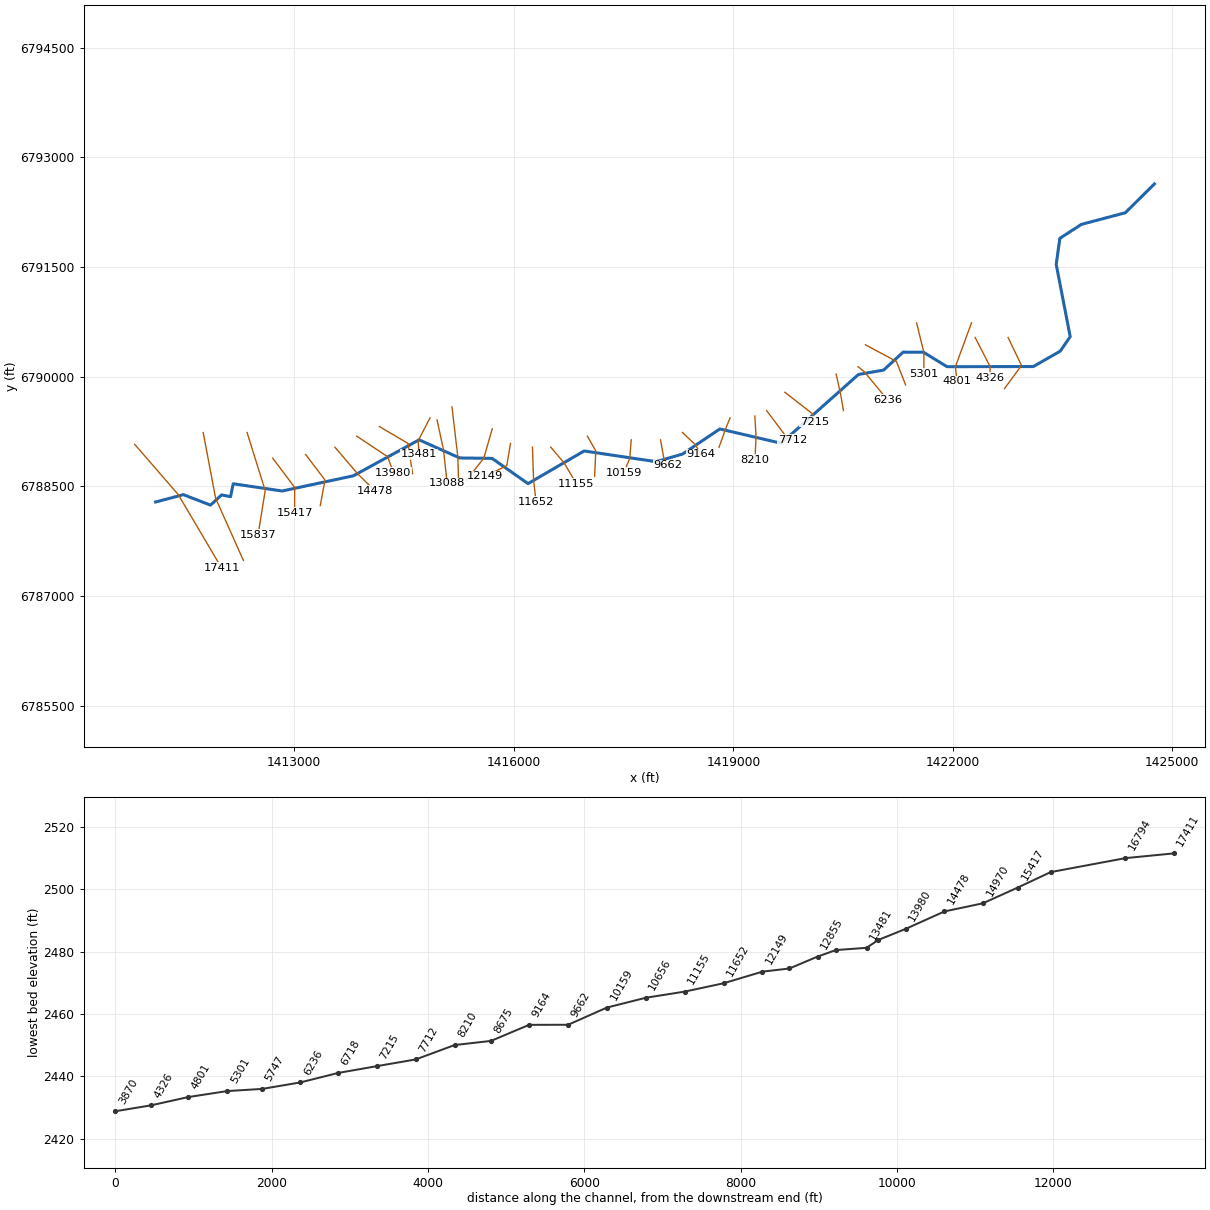
--- Bitter Creek Trib1.prj (project) ---

Proj Title=Bitter Creek Trib1 Base Level Engineering
Current Plan=p01
Default Exp/Contr=0.3,0.1
English Units
Geom File=g01
Flow File=f01
Plan File=p01
Y Axis Title=Elevation
X Axis Title(PF)=Main Channel Distance
X Axis Title(XS)=Station
BEGIN DESCRIPTION:
Bitter Creek Trib1
END DESCRIPTION:
DSS Export Rating Curves= 0
DSS Export Rating Curve Sorted= 0
DSS Export Volume Flow Curves= 0
DXF OffsetX= 0
DXF OffsetY= 0
DXF ScaleX= 1
DXF ScaleY= 10

--- Bitter Creek Trib1.p01 (plan) ---

Plan Title=Multiple Run
Short Identifier=Multiple
Geom File=g01
Flow File=f01
Subcritical Flow
K Sum by GR= 0
Std Step Tol= 0.01
Critical Tol= 0.01
Num of Std Step Trials= 20
Max Error Tol= 0.3
Flow Tol Ratio= 0.001
Split Flow NTrial= 30
Split Flow Tol= 0.02
Split Flow Ratio= 0.02
Log Output Level= 0
Friction Slope Method= 1
Unsteady Friction Slope Method= 2
Unsteady Bridges Friction Slope Method= 1
Parabolic Critical Depth
Global Vel Dist=  1 , 1 , 1
Global Log Level= 0
CheckData=True
Encroach Param= -1, 0, 0, 0
BEGIN DESCRIPTION:
Multiple Run
END DESCRIPTION:

--- Bitter Creek Trib1.f01 (steady flow) ---

Flow Title=Multiple
Program Version=4.10
Number of Profiles= 7
Profile Names=10-year,25-year,50-year,1pct_min,100-year,1pct_plu,500-year
River Rch & RM=Bitter Creek Tri,Reach-1         ,17411
     218     296     359     216     431     860     629
River Rch & RM=Bitter Creek Tri,Reach-1         ,13481
     471     674     845     526    1049    2093    1638
River Rch & RM=Bitter Creek Tri,Reach-1         ,8675
     544     785     989     618    1233    2461    1944
River Rch & RM=Bitter Creek Tri,Reach-1         ,8210
     673     982    1249     786    1569    3131    2513
River Rch & RM=Bitter Creek Tri,Reach-1         ,4801
     681     995    1265     797    1591    3175    2550
River Rch & RM=Bitter Creek Tri,Reach-1         ,3289
    1030    1516    1937    1224    2443    4875    3939
Boundary for River Rch & Prof#=Bitter Creek Tri,Reach-1         , 1
Up Type= 0
Dn Type= 3
Dn Slope=0.0055
Boundary for River Rch & Prof#=Bitter Creek Tri,Reach-1         , 2
Up Type= 0
Dn Type= 3
Dn Slope=0.0055
Boundary for River Rch & Prof#=Bitter Creek Tri,Reach-1         , 3
Up Type= 0
Dn Type= 3
Dn Slope=0.0055
Boundary for River Rch & Prof#=Bitter Creek Tri,Reach-1         , 4
Up Type= 0
Dn Type= 3
Dn Slope=0.0055
Boundary for River Rch & Prof#=Bitter Creek Tri,Reach-1         , 5
Up Type= 0
Dn Type= 3
Dn Slope=0.0055
Boundary for River Rch & Prof#=Bitter Creek Tri,Reach-1         , 6
Up Type= 0
Dn Type= 3
Dn Slope=0.0055
Boundary for River Rch & Prof#=Bitter Creek Tri,Reach-1         , 7
Up Type= 0
Dn Type= 3
Dn Slope=0.0055
DSS Import GetInterval= 0
DSS Import GetPeak= 0
DSS Import FillOption= 0

--- Bitter Creek Trib1.g01 (geometry) ---

Geom Title=Existing Conditions
Program Version=4.10

River Reach=Bitter Creek Tri,Reach-1
Reach XY= 30
        1411105.        6788288.      1411484.97      6788387.93
      1411855.21      6788245.02      1412006.71      6788384.64
      1412128.98       6788360.3      1412165.15      6788537.07
      1412834.97      6788438.07      1413808.23      6788646.24
        1414705.        6789138.      1415260.86      6788890.07
      1415703.45      6788884.25       1416194.3       6788538.7
      1416960.93      6788985.76       1417944.5      6788839.22
      1418307.29      6788943.84       1418815.5       6789286.8
      1419653.75      6789091.45      1420710.76      6790032.05
      1421053.45      6790091.75      1421320.83      6790337.34
      1421599.14      6790335.94      1421920.21      6790138.51
      1423099.06      6790140.25      1423468.24      6790351.62
      1423603.92      6790548.54      1423412.56        6791538.
       1423462.8      6791894.21      1423756.53      6792084.25
      1424357.43      6792243.52        1424755.        6792638.

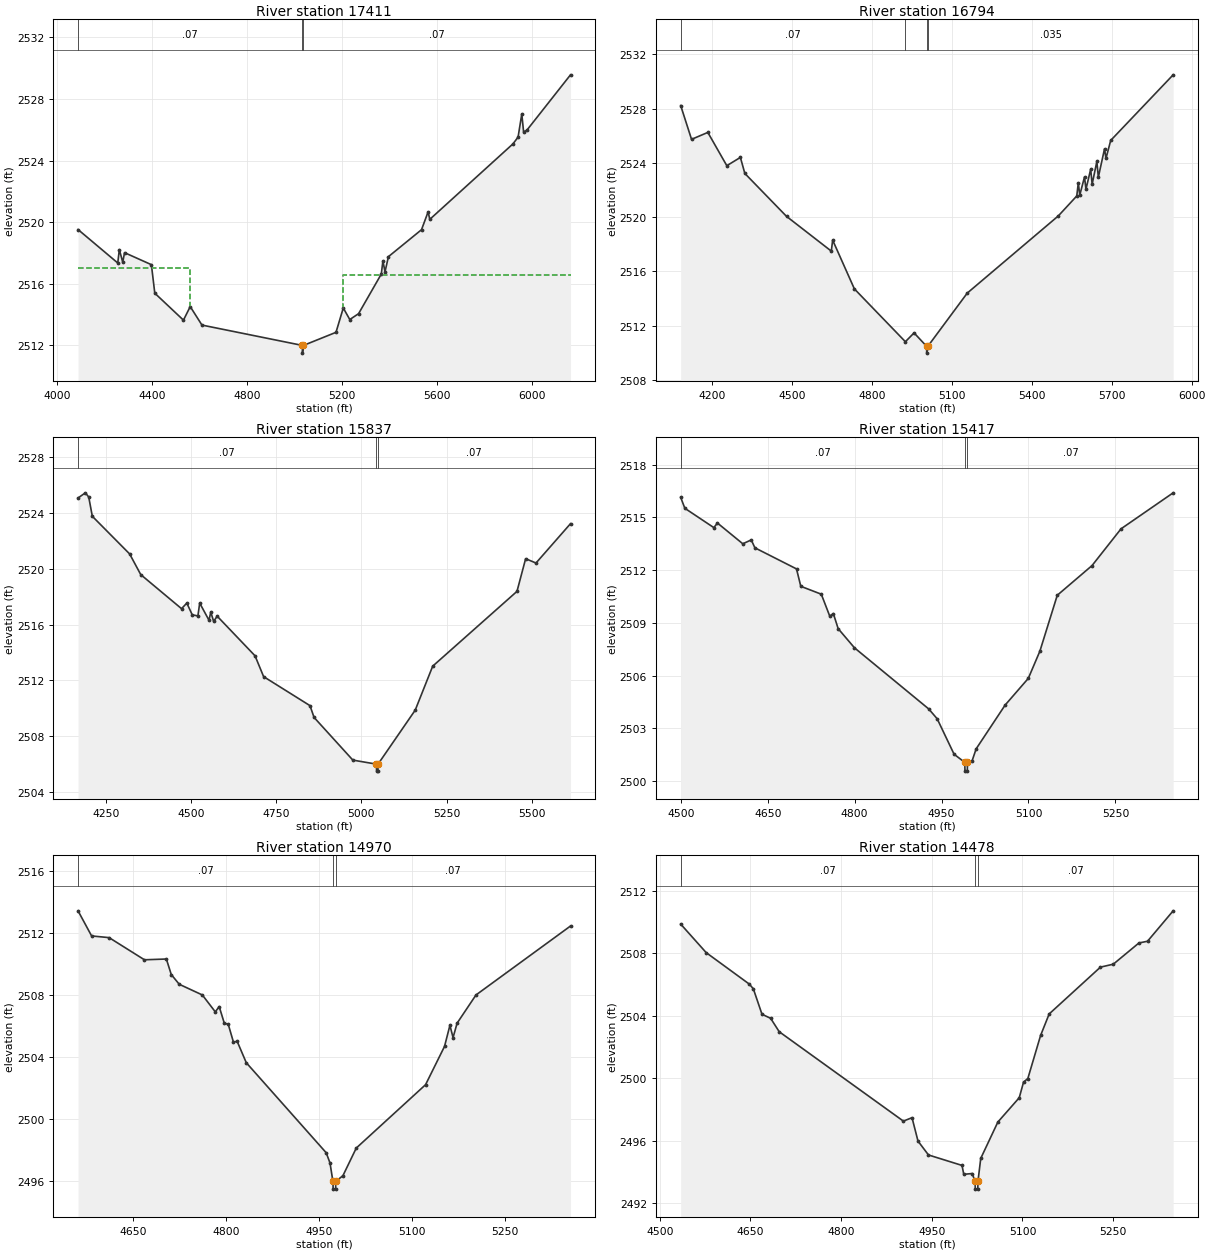
Type RM Length L Ch R = 1 ,17411   ,617,617,617
BEGIN DESCRIPTION:
Bitter Creek Trib1 32.0
END DESCRIPTION:
XS GIS Cut Line= 3
      1410818.49      6789077.03      1411415.05      6788388.12
      1412005.02      6787387.96
#Sta/Elev= 30
  4088.7 2519.52  4255.9 2517.35  4262.5 2518.22  4276.8  2517.4  4284.4 2518.02
  4397.4 2517.24  4411.7 2515.39  4532.3 2513.64  4560.8 2514.52  4610.2 2513.32
  5032.9    2512  5033.2  2511.5  5037.3    2512  5174.3 2512.85  5204.9 2514.43
  5232.3 2513.68  5269.3 2514.06  5364.9 2516.63  5371.7 2517.48  5380.6 2516.78
  5394.9 2517.76  5534.2 2519.51    5562 2520.67    5569 2520.18  5919.1 2525.08
  5940.6 2525.52  5956.2 2527.02  5963.8 2525.85  5977.7 2525.97  6161.2 2529.56
#Mann= 3 ,-1 , 0
  4088.7     .07       0  5032.9     .07       0  5037.3     .07       0
#XS Ineff= 2 , 0
         4560.91 2517.04 5203.05         2516.58
Permanent Ineff=
       F       F
Bank Sta=5032.9,5037.3
XS Rating Curve= 0 ,0
Exp/Cntr=0.3,0.1

Type RM Length L Ch R = 1 ,16794   ,957,957,957
BEGIN DESCRIPTION:
Bitter Creek Trib1 31.0
END DESCRIPTION:
XS GIS Cut Line= 3
        1411755.      6789238.01      1411925.34      6788337.58
      1412305.02      6787487.96
#Sta/Elev= 30
  4083.6 2528.22  4124.3 2525.73  4185.4 2526.24  4256.6 2523.79  4307.5  2524.4
  4324.2 2523.22  4480.5 2520.06  4648.5  2517.5  4653.6 2518.31    4735 2514.72
  4926.3 2510.83  4958.9 2511.48    5006 2510.49  5006.3 2509.99  5010.5 2510.49
  5158.4 2514.41  5499.8 2520.09  5569.1 2521.56  5574.9 2522.53  5580.3 2521.62
  5598.1 2522.96  5603.6 2522.06  5621.3 2523.53  5626.8 2522.43  5644.5 2524.11
    5650 2522.94  5673.2 2525.03  5678.7 2524.33  5696.4 2525.65  5930.6 2530.48
#Mann= 4 ,-1 , 0
  4083.6     .07       0  4926.3    .035       0    5006    .035       0
  5010.5    .035       0
Bank Sta=5006,5010.5
XS Rating Curve= 0 ,0
Exp/Cntr=0.3,0.1

Type RM Length L Ch R = 1 ,15837   ,420,420,420
BEGIN DESCRIPTION:
Bitter Creek Trib1 30.0
END DESCRIPTION:
XS GIS Cut Line= 3
        1412355.      6789238.01      1412602.55        6788444.
        1412505.        6787838.
#Sta/Elev= 30
  4168.3 2525.07  4189.8 2525.44  4199.7 2525.14  4210.2 2523.76  4319.8 2521.06
  4352.4 2519.58  4472.1 2517.14  4487.6 2517.54  4503.5  2516.7  4520.1 2516.62
  4525.4 2517.54  4552.7 2516.31  4557.9  2516.9  4566.3 2516.23  4576.8  2516.6
  4687.9 2513.76    4713 2512.27  4849.2 2510.19    4861 2509.35  4974.9 2506.29
  5044.3    2506  5044.6  2505.5  5048.6  2505.5  5048.9    2506    5158 2509.87
  5209.3 2513.02  5456.7 2518.38  5482.1 2520.72  5512.5 2520.41  5613.8 2523.23
#Mann= 3 ,-1 , 0
  4168.3     .07       0  5044.3     .07       0  5048.9     .07       0
Bank Sta=5044.3,5048.9
XS Rating Curve= 0 ,0
Exp/Cntr=0.3,0.1

Type RM Length L Ch R = 1 ,15417   ,447,447,447
BEGIN DESCRIPTION:
Bitter Creek Trib1 29.0
END DESCRIPTION:
XS GIS Cut Line= 3
      1412705.03      6788887.96      1413005.14      6788487.67
        1413005.      6788137.97
#Sta/Elev= 30
  4499.7 2516.14  4506.9 2515.52  4556.9 2514.42  4563.2 2514.68  4606.9  2513.5
  4621.5 2513.72  4627.8 2513.27  4699.6 2512.07    4707 2511.08  4742.4 2510.63
    4757 2509.38  4763.2 2509.53  4771.5 2508.67  4799.6 2507.58  4927.8  2504.1
  4942.4 2503.54  4971.6 2501.52    4990 2501.06  4990.4 2500.56  4994.4 2500.56
  4994.7 2501.06  5002.3 2501.11  5009.7 2501.83  5059.7 2504.32  5099.7 2505.84
  5119.7 2507.39  5149.7 2510.57  5209.7 2512.26  5259.7 2514.35  5349.7  2516.4
#Mann= 3 ,-1 , 0
  4499.7     .07       0    4990     .07       0  4994.7     .07       0
Bank Sta=4990,4994.7
XS Rating Curve= 0 ,0
Exp/Cntr=0.3,0.1

Type RM Length L Ch R = 1 ,14970   ,492,492,492
BEGIN DESCRIPTION:
Bitter Creek Trib1 28.0
END DESCRIPTION:
XS GIS Cut Line= 3
      1413154.97      6788938.04      1413420.18      6788587.57
        1413355.        6788238.
#Sta/Elev= 30
  4560.5 2513.46  4582.4 2511.84  4610.7 2511.73  4667.7  2510.3  4703.1 2510.35
    4711 2509.35  4723.9 2508.72  4761.2 2508.03  4782.1 2506.94  4788.4 2507.28
  4796.7  2506.2    4803 2506.14  4811.3    2505  4817.5 2505.03  4832.1 2503.66
  4961.1 2497.85  4967.3 2497.19    4972    2496  4972.4  2495.5  4976.4  2495.5
  4976.7    2496  4988.2 2496.37  5009.7 2498.15  5121.6 2502.24  5152.2 2504.71
  5160.9 2506.07    5166 2505.28  5172.5 2506.21    5203 2508.03  5355.6 2512.48
#Mann= 3 ,-1 , 0
  4560.5     .07       0    4972     .07       0  4976.7     .07       0
Bank Sta=4972,4976.7
XS Rating Curve= 0 ,0
Exp/Cntr=0.3,0.1

Type RM Length L Ch R = 1 ,14478   ,498,498,498
BEGIN DESCRIPTION:
Bitter Creek Trib1 27.0
END DESCRIPTION:
XS GIS Cut Line= 3
      1413555.02      6789037.98      1413856.65      6788683.56
      1414105.03      6788437.97
#Sta/Elev= 30
  4534.6 2509.88  4576.8 2508.05  4648.2 2506.03  4654.8 2505.73  4669.1  2504.1
  4683.4 2503.84  4697.6 2502.98    4903 2497.25  4917.3 2497.47 4927.19 2495.97
 4944.52 2495.08    5000 2494.41  5002.9 2493.84  5016.9 2493.89  5021.6 2493.39
    5022 2492.89  5026.1 2492.89  5026.4 2493.39    5031 2494.86  5059.3 2497.19
  5094.7 2498.75  5101.8 2499.75  5108.9 2499.98    5130 2502.74  5144.2 2504.12
    5229 2507.12  5250.3 2507.31  5292.7 2508.67  5306.9 2508.78  5349.3 2510.73
#Mann= 3 ,-1 , 0
  4534.6     .07       0  5021.6     .07       0  5026.4     .07       0
Bank Sta=5021.6,5026.4
XS Rating Curve= 0 ,0
Exp/Cntr=0.3,0.1

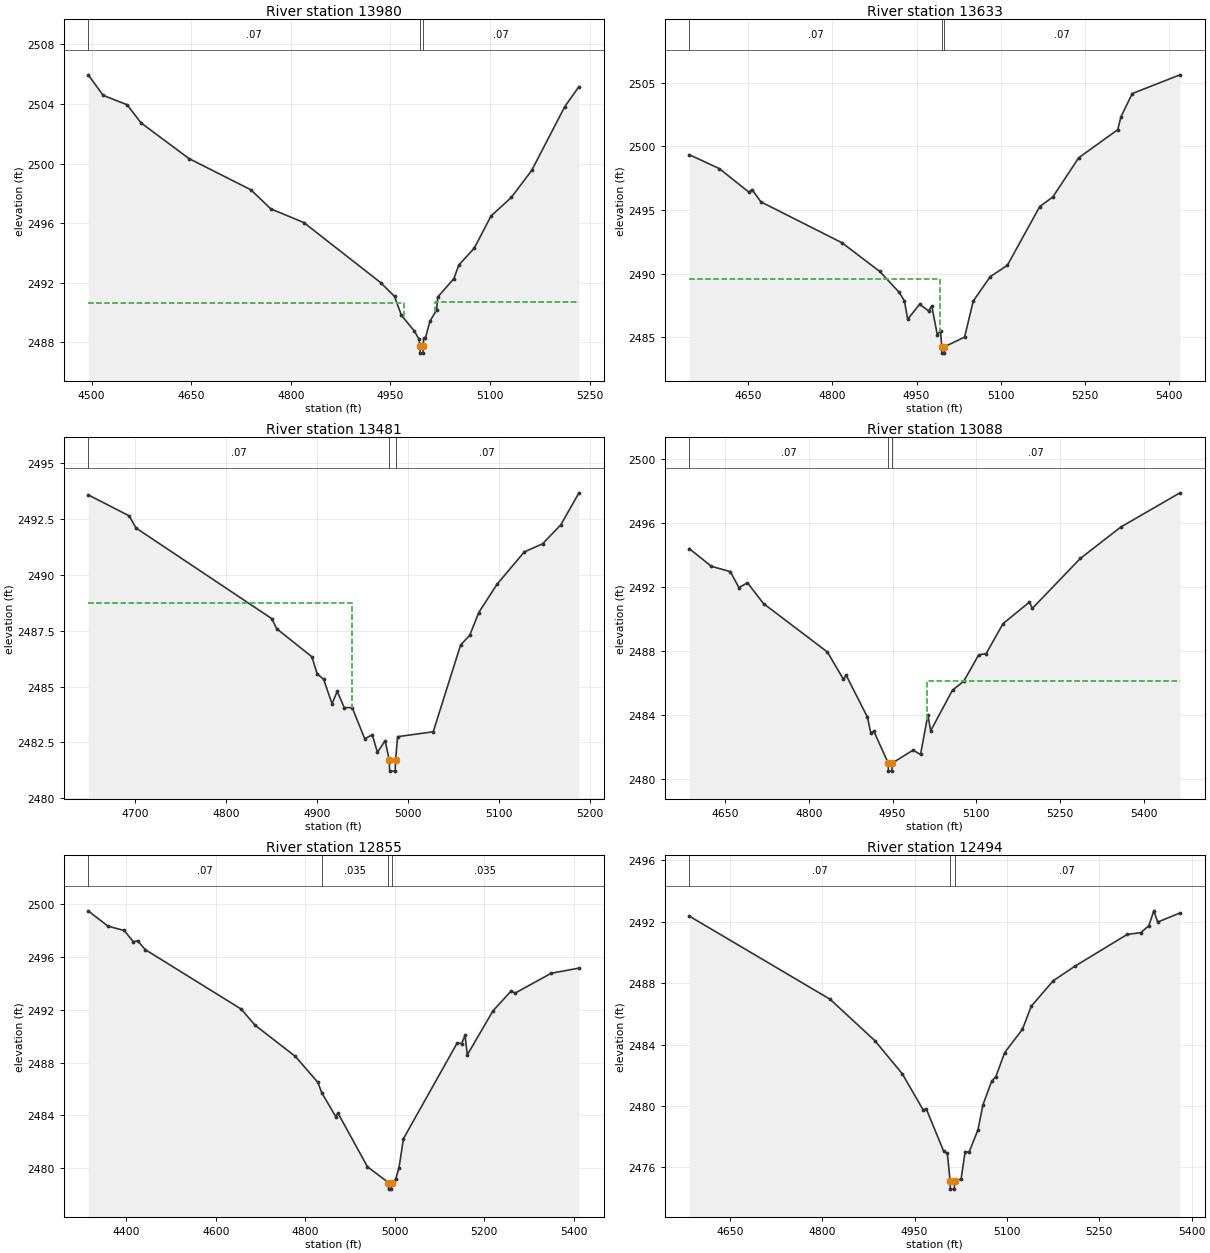
Type RM Length L Ch R = 1 ,13980   ,347,347,347
BEGIN DESCRIPTION:
Bitter Creek Trib1 26.0
END DESCRIPTION:
XS GIS Cut Line= 3
      1413854.98      6789188.02      1414275.09      6788907.78
      1414355.01      6788687.96
#Sta/Elev= 30
    4495 2505.96  4517.6 2504.58  4553.6 2503.95  4574.6 2502.73  4646.7 2500.34
  4739.9 2498.24  4769.9 2496.96  4819.6 2496.04  4935.2 2492.01  4956.2 2491.08
 4966.57 2489.81 4985.75 2488.77 4992.89 2488.22  4994.5 2487.77  4994.9 2487.27
    4999 2487.27  4999.4 2487.77    5000 2488.27  5002.5 2488.27  5009.7 2489.43
 5019.63 2490.17  5021.1 2491.03  5045.6 2492.28    5053 2493.19  5076.2 2494.32
  5101.5 2496.48  5132.1 2497.73  5162.7 2499.54  5212.6 2503.83  5233.9 2505.17
#Mann= 3 ,-1 , 0
    4495     .07       0  4994.5     .07       0  4999.4     .07       0
#XS Ineff= 2 , 0
         4970.29 2490.65 5017.65         2490.68
Permanent Ineff=
       F       F
Bank Sta=4994.5,4999.4
XS Rating Curve= 0 ,0
Exp/Cntr=0.3,0.1

Type RM Length L Ch R = 1 ,13633   ,152,152,152
BEGIN DESCRIPTION:
Bitter Creek Trib1 4270
END DESCRIPTION:
XS GIS Cut Line= 3
      1414163.25      6789319.82      1414554.85      6789088.35
      1414616.36      6788673.99
#Sta/Elev= 30
  4545.1 2499.35  4598.6 2498.26  4651.3 2496.41  4657.1 2496.61  4672.8 2495.64
  4817.1 2492.43    4884 2490.19  4918.9 2488.54  4928.3 2487.87  4934.1 2486.43
  4955.5  2487.6  4971.2 2487.08    4977 2487.46  4986.8 2485.21  4992.6  2485.5
  4994.7 2484.26  4995.1 2483.76  4999.3 2483.76  4999.6 2484.26  5035.4 2485.02
  5050.9 2487.86  5081.2 2489.77  5111.6 2490.66  5169.2 2495.27  5192.4 2496.02
  5238.7 2499.11  5308.1 2501.31  5313.8 2502.32    5334 2504.15  5418.9 2505.62
#Mann= 3 ,-1 , 0
  4545.1     .07       0  4994.7     .07       0  4999.6     .07       0
#XS Ineff= 2 , 0
         4991.18 2489.56
Permanent Ineff=
       F       F
Bank Sta=4994.7,4999.6
XS Rating Curve= 0 ,0
Exp/Cntr=0.3,0.1

Type RM Length L Ch R = 1 ,13481   ,393,393,393
BEGIN DESCRIPTION:
Bitter Creek Trib1 25.0
END DESCRIPTION:
XS GIS Cut Line= 3
      1414855.01      6789438.02      1414693.18      6789125.54
        1414705.      6788938.01
#Sta/Elev= 30
  4648.1 2493.57  4693.2 2492.63  4700.6 2492.09  4849.9 2488.04  4855.6 2487.58
  4894.2 2486.33  4899.8 2485.58  4907.1 2485.32  4916.3 2484.23    4922 2484.79
  4929.7 2484.06  4938.5 2484.06  4952.2 2482.67  4960.6 2482.84  4966.2 2482.06
  4974.7 2482.58  4979.2 2481.72  4979.7 2481.22  4985.7 2481.22  4986.2 2481.72
  4988.4 2482.76  5027.6 2482.98  5057.7 2486.86  5067.7 2487.29  5077.7 2488.31
  5097.7 2489.57  5127.8 2491.02  5147.8 2491.38  5167.9 2492.23  5187.9 2493.66
#Mann= 3 ,-1 , 0
  4648.1     .07       0  4979.2     .07       0  4986.2     .07       0
#XS Ineff= 2 , 0
         4938.68 2488.73
Permanent Ineff=
       F       F
Bank Sta=4979.2,4986.2
XS Rating Curve= 0 ,0
Exp/Cntr=0.3,0.1

Type RM Length L Ch R = 1 ,13088   ,233,233,233
BEGIN DESCRIPTION:
Bitter Creek Trib1 4168
END DESCRIPTION:
XS GIS Cut Line= 3
      1414951.23      6789410.03      1415038.43      6789004.91
      1415089.25       6788542.9
#Sta/Elev= 30
  4585.6  2494.4  4625.4 2493.29  4659.3 2492.96  4674.7 2491.96    4690 2492.26
  4718.9 2490.96  4833.2 2487.94  4861.8 2486.24  4866.9 2486.48  4904.8 2483.88
  4911.1 2482.87  4916.3    2483  4942.1    2481  4942.6  2480.5  4948.7  2480.5
  4949.2    2481  4986.6 2481.81    5000 2481.54  5013.2 2484.01  5018.2 2483.02
  5057.3 2485.56  5077.4 2486.11  5104.2 2487.76  5117.6 2487.84  5147.8 2489.71
  5195.2 2491.06  5200.2 2490.66  5286.2 2493.78  5359.1 2495.75  5464.8 2497.88
#Mann= 3 ,-1 , 0
  4585.6     .07       0  4942.1     .07       0  4949.2     .07       0
#XS Ineff= 2 , 0
                         5011.57         2486.15
Permanent Ineff=
       F       F
Bank Sta=4942.1,4949.2
XS Rating Curve= 0 ,0
Exp/Cntr=0.3,0.1

Type RM Length L Ch R = 1 ,12855   ,361,361,361
BEGIN DESCRIPTION:
Bitter Creek Trib1 24.0
END DESCRIPTION:
XS GIS Cut Line= 3
        1415155.      6789587.98      1415234.85      6788907.65
      1415248.11      6788495.96
#Sta/Elev= 30
    4315 2499.49  4359.1 2498.33  4395.5    2498  4415.7 2497.15  4425.7 2497.22
  4442.2 2496.56  4657.3 2492.04  4687.5 2490.84  4778.1 2488.46  4828.5 2486.49
  4836.9 2485.72  4868.1 2483.91  4873.2 2484.17  4939.2  2480.1    4986 2478.91
  4986.5 2478.41  4992.6 2478.41  4993.1 2478.91  5002.3 2479.16  5009.7 2480.04
  5019.7 2482.24  5139.7 2489.48  5149.7 2489.44  5157.3 2490.06  5162.3 2488.58
  5219.8 2491.92  5259.8  2493.4  5269.8 2493.27  5349.8 2494.76  5411.9 2495.15
#Mann= 4 ,-1 , 0
    4315     .07       0  4836.9    .035       0    4986    .035       0
  4993.1    .035       0
Bank Sta=4986,4993.1
XS Rating Curve= 0 ,0
Exp/Cntr=0.3,0.1

Type RM Length L Ch R = 1 ,12494   ,345,345,345
BEGIN DESCRIPTION:
Bitter Creek Trib1 23.0
END DESCRIPTION:
XS GIS Cut Line= 3
      1415705.01      6789288.04      1415590.02      6788888.04
      1415355.02      6788588.02
#Sta/Elev= 30
  4583.8 2492.37  4812.8 2486.95  4885.6 2484.25    4930  2482.1  4963.7 2479.76
  4968.9 2479.82  4997.4 2477.04  5003.2 2476.93  5007.7 2475.09  5008.2 2474.59
  5014.4 2474.59  5014.9 2475.09  5025.5 2475.25  5032.1 2477.03  5038.5    2477
  5052.9 2478.45  5061.1 2480.09  5075.5 2481.65  5081.9  2481.9  5096.3 2483.48
  5125.2    2485  5139.7 2486.51    5175 2488.15  5210.2  2489.1  5295.2 2491.17
  5317.6 2491.29  5330.5 2491.74  5338.6 2492.71    5345 2491.98  5381.1 2492.57
#Mann= 3 ,-1 , 0
  4583.8     .07       0  5007.7     .07       0  5014.9     .07       0
Bank Sta=5007.7,5014.9
XS Rating Curve= 0 ,0
Exp/Cntr=0.3,0.1

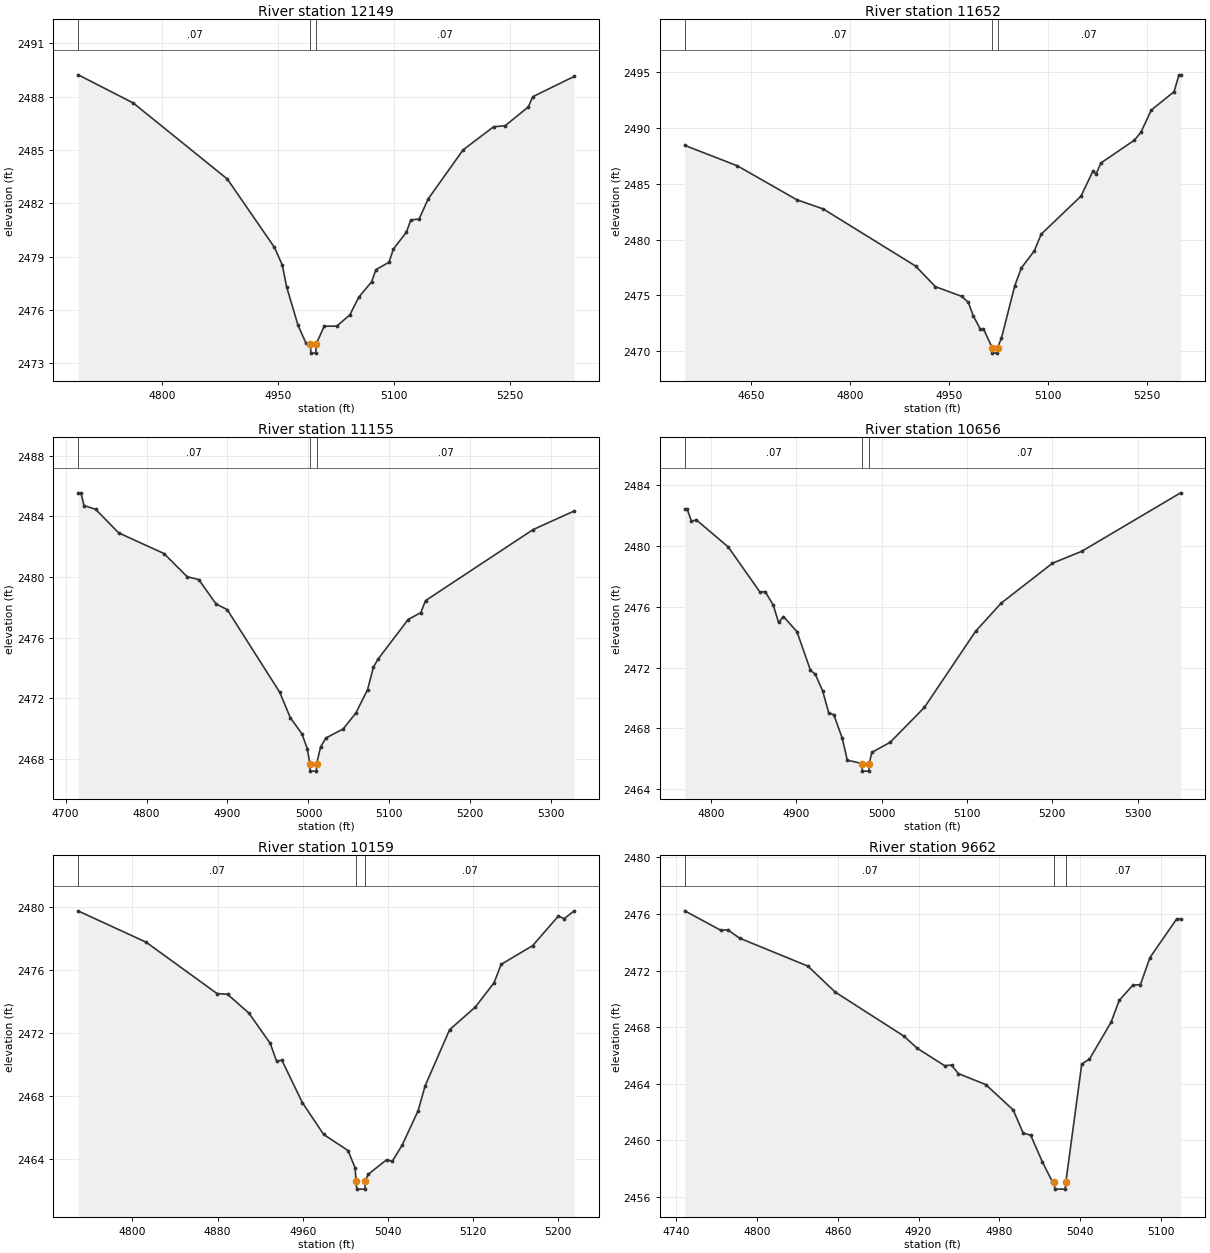
Type RM Length L Ch R = 1 ,12149   ,497,497,497
BEGIN DESCRIPTION:
Bitter Creek Trib1 22.0
END DESCRIPTION:
XS GIS Cut Line= 3
        1415955.      6789087.99      1415903.57      6788784.11
        1415605.        6788638.
#Sta/Elev= 30
  4691.8 2489.22  4762.8 2487.64  4884.5 2483.36  4945.3 2479.52  4955.5 2478.52
    4961  2477.3  4975.8 2475.14  4985.9 2474.15  4991.8 2474.08  4992.3 2473.58
  4998.6 2473.58  4999.1 2474.08  5009.5 2475.09  5025.8  2475.1  5042.7 2475.73
  5054.1 2476.72  5070.8 2477.59  5076.3 2478.27  5093.3 2478.69  5098.9 2479.43
  5115.8 2480.38  5121.4 2481.07    5132 2481.11  5143.9 2482.25  5188.9    2485
  5228.3  2486.3  5243.3 2486.36  5273.3 2487.42  5278.9 2487.99  5332.4 2489.13
#Mann= 3 ,-1 , 0
  4691.8     .07       0  4991.8     .07       0  4999.1     .07       0
Bank Sta=4991.8,4999.1
XS Rating Curve= 0 ,0
Exp/Cntr=0.3,0.1

Type RM Length L Ch R = 1 ,11652   ,497,497,497
BEGIN DESCRIPTION:
Bitter Creek Trib1 21.0
END DESCRIPTION:
XS GIS Cut Line= 3
        1416255.      6789037.96      1416270.39      6788587.03
        1416305.      6788288.02
#Sta/Elev= 30
  4548.8 2488.41  4628.8 2486.58  4718.9 2483.55  4758.9 2482.73    4899 2477.63
    4929 2475.79    4969 2474.92    4979 2474.39  4986.3 2473.21    4997 2472.02
    5002 2472.02    5015 2470.35  5015.5 2469.85  5022.8 2469.85  5023.3 2470.35
  5029.2 2471.17  5049.4 2475.86  5059.4 2477.45  5079.1 2478.99  5089.6 2480.48
    5150 2483.88  5167.8 2486.09  5172.9 2485.87  5180.2 2486.84  5230.6 2488.86
  5240.6 2489.56  5256.6 2491.57    5291  2493.2  5298.5 2494.71    5301 2494.71
#Mann= 3 ,-1 , 0
  4548.8     .07       0    5015     .07       0  5023.3     .07       0
Bank Sta=5015,5023.3
XS Rating Curve= 0 ,0
Exp/Cntr=0.3,0.1

Type RM Length L Ch R = 1 ,11155   ,499,499,499
BEGIN DESCRIPTION:
Bitter Creek Trib1 20.0
END DESCRIPTION:
XS GIS Cut Line= 3
      1416504.97      6789038.03      1416688.67      6788820.92
      1416855.01      6788537.99
#Sta/Elev= 30
  4715.6 2485.56  4718.9 2485.56  4722.8 2484.72  4737.1 2484.47  4765.7 2482.91
  4821.6 2481.55  4850.2 2480.02  4864.5 2479.83  4885.9 2478.22  4899.6 2477.85
  4964.5 2472.39  4977.6 2470.71  4991.9 2469.65  4998.6 2468.66  5001.7 2467.68
  5002.2 2467.18  5009.7 2467.18  5010.2 2467.68    5015 2468.78  5021.6 2469.37
    5043 2469.97  5058.7 2471.03    5073 2472.56  5080.2 2474.04    5086 2474.58
  5123.1 2477.19  5138.8 2477.65  5144.6 2478.44  5277.4 2483.13  5328.2 2484.36
#Mann= 3 ,-1 , 0
  4715.6     .07       0  5001.7     .07       0  5010.2     .07       0
Bank Sta=5001.7,5010.2
XS Rating Curve= 0 ,0
Exp/Cntr=0.3,0.1

Type RM Length L Ch R = 1 ,10656   ,497,497,497
BEGIN DESCRIPTION:
Bitter Creek Trib1 19.0
END DESCRIPTION:
XS GIS Cut Line= 3
        1417005.        6789188.        1417120.      6788988.01
        1417105.      6788638.03
#Sta/Elev= 30
  4769.3  2482.4  4772.2  2482.4  4777.2 2481.61    4783 2481.69  4820.3 2479.92
  4857.7 2476.94  4863.5 2476.99  4873.1  2476.1  4879.3 2474.96    4885 2475.35
  4900.8 2474.36  4916.6 2471.83  4922.4 2471.55  4930.8 2470.49  4938.2    2469
    4944 2468.91  4953.9 2467.36  4959.8 2465.92    4977  2465.7  4977.5  2465.2
  4985.1  2465.2  4985.6  2465.7  4988.5 2466.43    5010 2467.09  5050.1 2469.38
  5110.1 2474.38  5140.1 2476.23  5200.2 2478.85  5234.4 2479.63  5350.3 2483.47
#Mann= 3 ,-1 , 0
  4769.3     .07       0    4977     .07       0  4985.6     .07       0
Bank Sta=4977,4985.6
XS Rating Curve= 0 ,0
Exp/Cntr=0.3,0.1

Type RM Length L Ch R = 1 ,10159   ,497,497,497
BEGIN DESCRIPTION:
Bitter Creek Trib1 18.0
END DESCRIPTION:
XS GIS Cut Line= 3
        1417605.      6789137.95       1417584.9      6788887.76
      1417505.02      6788688.04
#Sta/Elev= 30
    4749 2479.72  4812.8 2477.74  4879.4 2474.48  4889.4 2474.43  4909.5 2473.23
  4929.5 2471.31  4935.4 2470.19  4940.4 2470.25  4959.6 2467.56  4979.7 2465.53
  5002.6 2464.51  5009.2 2463.41  5010.2 2462.56  5010.7 2462.06  5018.4 2462.06
  5018.9 2462.56  5021.3 2462.99  5038.8 2463.92  5044.2 2463.83  5053.6 2464.87
  5068.4 2467.03  5075.1 2468.63    5098 2472.18  5122.2 2473.62  5139.8 2475.16
  5146.5 2476.33  5176.1 2477.52  5200.3  2479.4  5205.7 2479.23  5215.1 2479.73
#Mann= 3 ,-1 , 0
    4749     .07       0  5010.2     .07       0  5018.9     .07       0
Bank Sta=5010.2,5018.9
XS Rating Curve= 0 ,0
Exp/Cntr=0.3,0.1

Type RM Length L Ch R = 1 ,9662    ,498,498,498
BEGIN DESCRIPTION:
Bitter Creek Trib1 17.0
END DESCRIPTION:
XS GIS Cut Line= 3
      1418004.99      6789138.04      1418049.82      6788888.43
        1418105.      6788787.99
#Sta/Elev= 30
  4746.4 2476.22  4773.3 2474.84  4778.4 2474.88  4787.1 2474.29  4837.9 2472.31
  4858.2 2470.47    4909 2467.37  4919.2 2466.49  4939.4 2465.27  4944.5 2465.31
  4949.6 2464.71    4970 2463.93  4990.3 2462.14  4997.7 2460.51  5003.3 2460.35
  5011.9 2458.48  5019.4 2457.06  5020.7 2457.04  5021.2 2456.54  5028.9 2456.54
  5029.4 2457.04  5041.2 2465.39  5046.9 2465.73    5063 2468.35    5069 2469.89
    5079 2470.95  5084.8 2471.01  5091.8 2472.91  5111.7 2475.65  5114.6 2475.65
#Mann= 3 ,-1 , 0
  4746.4     .07       0  5020.7     .07       0  5029.4     .07       0
Bank Sta=5020.7,5029.4
XS Rating Curve= 0 ,0
Exp/Cntr=0.3,0.1

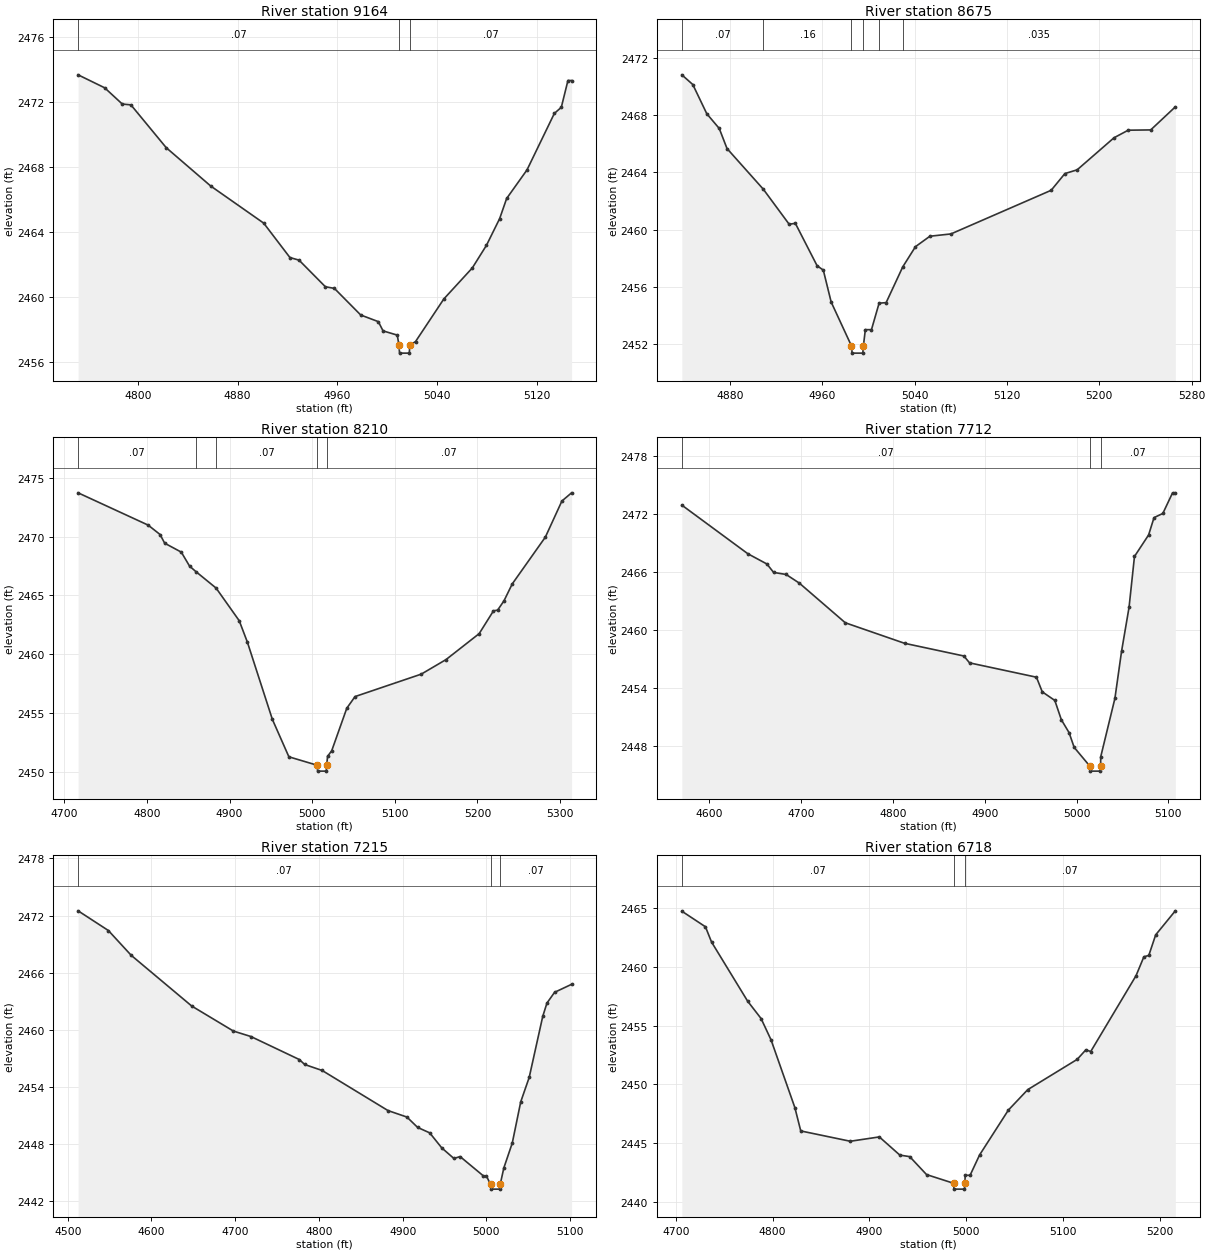
Type RM Length L Ch R = 1 ,9164    ,489,489,489
BEGIN DESCRIPTION:
Bitter Creek Trib1 16.0
END DESCRIPTION:
XS GIS Cut Line= 3
      1418304.97      6789238.03      1418485.07      6789067.82
      1418555.02      6788937.96
#Sta/Elev= 30
  4752.2 2473.67  4773.5 2472.87  4787.6 2471.87  4794.5 2471.82  4822.8 2469.18
  4858.4 2466.82  4900.9 2464.53  4921.9 2462.41  4929.2 2462.25  4950.3 2460.61
  4957.5 2460.51  4978.6 2458.87  4992.7 2458.46  4996.5 2457.89  5007.9 2457.63
  5009.2 2457.02  5009.7 2456.52  5017.5 2456.52    5018 2457.02  5022.5 2457.23
  5045.2 2459.86    5068 2461.77  5079.3 2463.16  5089.9 2464.81  5095.5 2466.05
  5111.8 2467.81  5133.7 2471.29  5139.3 2471.67  5144.6 2473.32  5147.5 2473.32
#Mann= 3 ,-1 , 0
  4752.2     .07       0  5009.2     .07       0    5018     .07       0
Bank Sta=5009.2,5018
XS Rating Curve= 0 ,0
Exp/Cntr=0.3,0.1

Type RM Length L Ch R = 1 ,8675    ,465,465,465
BEGIN DESCRIPTION:
Bitter Creek Trib1 15.0
END DESCRIPTION:
XS GIS Cut Line= 3
      1418955.01      6789438.04      1418894.95      6789288.12
        1418805.        6789038.
#Sta/Elev= 30
  4838.5 2470.81    4848 2470.13  4860.1 2468.09  4870.9 2467.06  4877.6 2465.66
    4909 2462.82  4931.4 2460.37  4936.8 2460.43  4955.6 2457.47    4961 2457.16
  4967.8 2454.93  4985.4 2451.86  4985.9 2451.36  4995.2 2451.36  4995.7 2451.86
  4997.4    2453  5002.7    2453  5009.3 2454.85  5015.4 2454.89  5029.8 2457.39
  5040.8  2458.8  5053.3 2459.53  5071.5 2459.69  5158.3 2462.74  5170.2 2463.91
  5180.8 2464.17  5212.7 2466.41    5225 2466.94  5244.5 2466.96  5265.8 2468.57
#Mann= 6 ,-1 , 0
  4838.5     .07       0    4909     .16       0  4985.4     .07       0
  4995.7     .16       0  5009.3     .07       0  5029.8    .035       0
Bank Sta=4985.4,4995.7
XS Rating Curve= 0 ,0
Exp/Cntr=0.3,0.1

Type RM Length L Ch R = 1 ,8210    ,498,498,498
BEGIN DESCRIPTION:
Bitter Creek Trib1 14.0
END DESCRIPTION:
XS GIS Cut Line= 3
      1419294.12      6789462.63      1419311.01      6789179.84
      1419295.42      6788866.33
#Sta/Elev= 30
  4716.7 2473.74  4801.5 2470.99  4815.9 2470.19  4821.5 2469.45  4841.6 2468.69
  4851.6  2467.5  4859.3 2467.03  4883.7 2465.63  4911.7 2462.85  4921.7    2461
  4951.8 2454.45  4971.8 2451.26  5006.1 2450.54  5006.6 2450.04  5017.1 2450.04
  5017.6 2450.54  5018.6  2451.3  5023.6 2451.77  5041.9  2455.4  5051.9 2456.39
    5132  2458.3    5162 2459.54  5202.1 2461.75  5219.4 2463.69  5224.4 2463.75
  5232.1 2464.54  5242.1 2465.98  5282.2 2469.97  5302.2 2473.04  5313.9 2473.74
#Mann= 5 ,-1 , 0
  4716.7     .07       0  4859.3     .16       0  4883.7     .07       0
  5006.1     .07       0  5017.6     .07       0
Bank Sta=5006.1,5017.6
XS Rating Curve= 0 ,0
Exp/Cntr=0.3,0.1

Type RM Length L Ch R = 1 ,7712    ,497,497,497
BEGIN DESCRIPTION:
Bitter Creek Trib1 13.0
END DESCRIPTION:
XS GIS Cut Line= 3
      1419454.99      6789538.02      1419713.17      6789194.03
      1419805.02      6789137.99
#Sta/Elev= 30
  4569.9 2472.89  4641.8 2467.87  4662.6 2466.81  4669.9 2465.94  4683.5 2465.73
    4698 2464.83    4748 2460.74  4812.6 2458.62  4877.2 2457.31  4883.4  2456.6
  4956.3 2455.12  4962.6 2453.61  4976.3 2452.72  4983.4 2450.73  4991.8  2449.4
  4997.4 2447.87  5014.6 2445.92  5015.1 2445.42  5025.7 2445.42  5026.2 2445.92
  5026.3 2446.89  5041.8 2452.94    5049 2457.78  5057.2 2462.34  5063.1 2467.59
  5078.5 2469.81  5084.4  2471.6    5094 2472.03  5104.6 2474.16  5107.6 2474.16
#Mann= 3 ,-1 , 0
  4569.9     .07       0  5014.6     .07       0  5026.2     .07       0
Bank Sta=5014.6,5026.2
XS Rating Curve= 0 ,0
Exp/Cntr=0.3,0.1

Type RM Length L Ch R = 1 ,7215    ,497,497,497
BEGIN DESCRIPTION:
Bitter Creek Trib1 12.0
END DESCRIPTION:
XS GIS Cut Line= 3
      1419704.99      6789788.01      1420089.78      6789488.53
        1420105.      6789387.98
#Sta/Elev= 30
  4512.4  2472.5  4548.6 2470.43  4575.8 2467.83  4648.1  2462.5  4697.9 2459.87
  4718.7  2459.3  4776.6 2456.88    4783 2456.36  4803.9 2455.73  4882.5 2451.52
  4905.1 2450.84  4917.9 2449.75  4932.3 2449.18  4946.7  2447.6  4961.2 2446.49
  4968.6 2446.69  4996.4 2444.66    5000 2444.66  5004.9 2443.77  5005.4 2443.27
    5016 2443.27  5016.5 2443.77  5020.8 2445.49  5030.9 2448.11    5041 2452.44
  5051.1    2455  5067.3 2461.42  5072.3 2462.81  5081.4 2463.94  5101.7 2464.78
#Mann= 3 ,-1 , 0
  4512.4     .07       0  5004.9     .07       0  5016.5     .07       0
Bank Sta=5004.9,5016.5
XS Rating Curve= 0 ,0
Exp/Cntr=0.3,0.1

Type RM Length L Ch R = 1 ,6718    ,482,482,482
BEGIN DESCRIPTION:
Bitter Creek Trib1 11.0
END DESCRIPTION:
XS GIS Cut Line= 3
        1420405.      6790037.99      1420468.38      6789751.21
      1420504.99      6789538.03
#Sta/Elev= 30
  4706.3 2464.77  4730.7 2463.44    4737 2462.14  4774.3  2457.1  4788.2 2455.62
  4798.5  2453.8  4823.1 2448.03  4829.2 2446.04  4880.4 2445.16  4910.4 2445.53
  4931.6 2443.98  4941.8 2443.85  4959.2 2442.32  4987.1 2441.58  4987.6 2441.08
  4998.4 2441.08  4998.9 2441.58  4999.1 2442.26  5004.2 2442.26    5014 2443.99
  5043.8 2447.82  5063.8 2449.56  5114.9 2452.14  5123.8 2452.95  5128.9 2452.81
  5175.7 2459.27  5183.8 2460.88  5188.9    2461    5196 2462.75  5216.3  2464.8
#Mann= 3 ,-1 , 0
  4706.3     .07       0  4987.1     .07       0  4998.9     .07       0
Bank Sta=4987.1,4998.9
XS Rating Curve= 0 ,0
Exp/Cntr=0.3,0.1

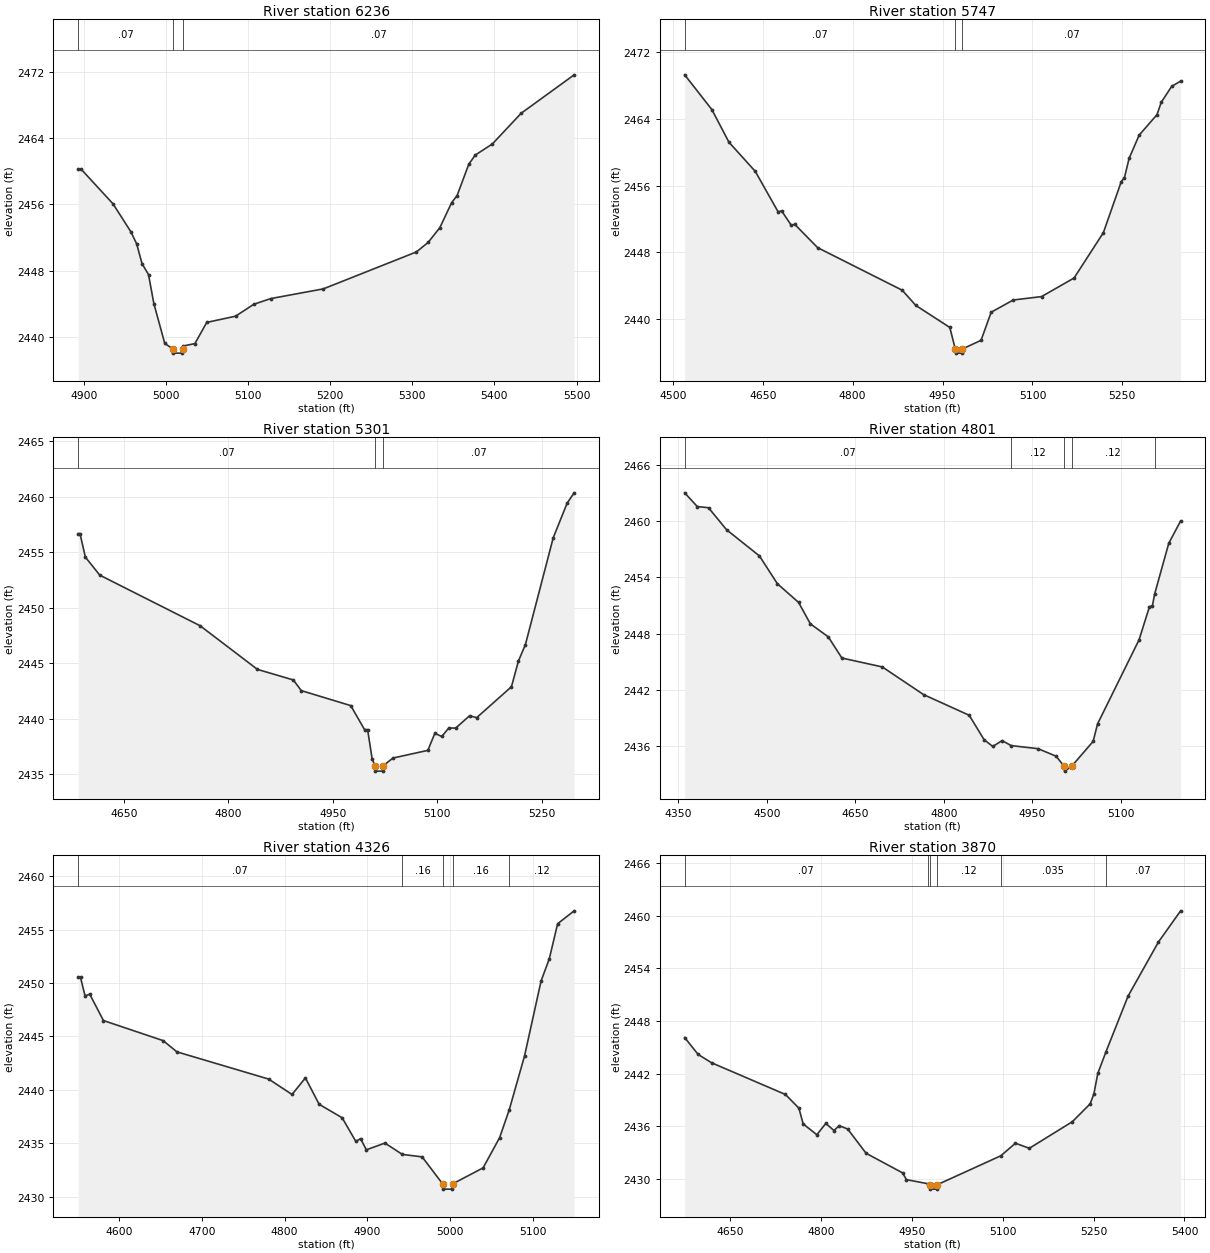
Type RM Length L Ch R = 1 ,6236    ,489,489,489
BEGIN DESCRIPTION:
Bitter Creek Trib1 10.0
END DESCRIPTION:
XS GIS Cut Line= 3
      1420704.98      6790138.02      1420788.31      6790071.22
      1421104.97      6789688.03
#Sta/Elev= 30
  4893.2  2460.3  4896.4  2460.3  4935.6 2456.08  4957.3 2452.71  4964.4 2451.24
  4970.9 2448.86  4978.8 2447.54  4985.3 2444.04  4998.6 2439.22  5008.6 2438.55
  5009.1 2438.05  5019.9 2438.05  5020.4 2438.55    5021 2438.91  5035.3  2439.2
  5049.7 2441.76  5084.8 2442.51    5107 2443.95  5127.8 2444.64  5191.7 2445.81
    5305 2450.27  5319.3 2451.42  5333.6 2453.21    5348 2456.24  5354.5 2457.06
  5368.8 2460.87  5376.7 2461.97  5397.5 2463.31  5432.6 2467.02  5497.1 2471.66
#Mann= 3 ,-1 , 0
  4893.2     .07       0  5008.6     .07       0  5020.4     .07       0
Bank Sta=5008.6,5020.4
XS Rating Curve= 0 ,0
Exp/Cntr=0.3,0.1

Type RM Length L Ch R = 1 ,5747    ,446,446,446
BEGIN DESCRIPTION:
Bitter Creek Trib1 9.0
END DESCRIPTION:
XS GIS Cut Line= 3
        1420805.        6790438.      1421228.41      6790211.26
      1421355.01      6789887.96
#Sta/Elev= 30
  4519.7 2469.24  4565.1 2465.08  4593.6 2461.18  4637.5  2457.7  4675.7 2452.85
  4681.4 2452.98  4697.6 2451.25  4703.3 2451.37  4741.5 2448.58  4882.7 2443.49
  4905.4 2441.67  4962.1 2439.04  4971.2 2436.47  4971.7 2435.97  4982.6 2435.97
  4983.1 2436.47  5014.2  2437.5  5031.1 2440.86  5067.9 2442.32  5115.2 2442.73
  5169.4 2444.95  5218.3 2450.37  5248.2 2456.48  5253.5 2456.96  5261.2 2459.24
    5278 2462.03  5307.8 2464.48  5314.9 2465.96  5332.3 2467.86  5347.2 2468.49
#Mann= 3 ,-1 , 0
  4519.7     .07       0  4971.2     .07       0  4983.1     .07       0
Bank Sta=4971.2,4983.1
XS Rating Curve= 0 ,0
Exp/Cntr=0.3,0.1

Type RM Length L Ch R = 1 ,5301    ,500,500,500
BEGIN DESCRIPTION:
Bitter Creek Trib1 8.0
END DESCRIPTION:
XS GIS Cut Line= 3
        1421505.        6790738.      1421603.53      6790334.45
        1421605.      6790037.96
#Sta/Elev= 30
  4584.6 2456.66  4587.2 2456.66  4594.9 2454.55  4615.5 2452.93  4759.6 2448.37
  4841.9 2444.44  4893.4 2443.49  4904.8 2442.53  4975.8 2441.18  4995.6 2439.02
    5000 2439.02  5006.5 2436.39  5010.4 2435.78  5010.9 2435.28  5022.1 2435.28
  5022.6 2435.78  5036.5 2436.46  5086.5 2437.15  5096.5 2438.68  5106.5  2438.4
  5116.5 2439.16  5126.5 2439.16  5146.5 2440.27  5156.5 2440.09  5206.5 2442.88
  5216.5 2445.19  5226.5 2446.67  5266.5  2456.3  5286.5 2459.42  5296.5 2460.34
#Mann= 3 ,-1 , 0
  4584.6     .07       0  5010.4     .07       0  5022.6     .07       0
Bank Sta=5010.4,5022.6
XS Rating Curve= 0 ,0
Exp/Cntr=0.3,0.1

Type RM Length L Ch R = 1 ,4801    ,475,475,475
BEGIN DESCRIPTION:
Bitter Creek Trib1 7.0
END DESCRIPTION:
XS GIS Cut Line= 3
      1422255.01      6790738.02      1422034.99      6790137.98
        1422055.      6789937.98
#Sta/Elev= 30
  4360.9    2463  4382.2 2461.54  4401.3 2461.41  4431.8 2459.07  4487.5 2456.28
    4518 2453.31  4553.8 2451.33  4573.7 2449.05  4604.2 2447.65  4627.2  2445.4
  4695.7 2444.45  4765.7  2441.5  4842.9  2439.3  4868.1  2436.7  4882.8 2435.98
  4898.6  2436.6    4914 2436.07  4959.6 2435.74  4990.1 2434.94  5003.9 2433.85
  5004.4 2433.35  5016.2 2433.85  5052.8 2436.52  5060.3 2438.38  5130.6 2447.34
  5148.2 2450.86  5153.3 2450.99  5156.9  2452.2  5180.9 2457.62    5201    2460
#Mann= 5 ,-1 , 0
  4360.9     .07       0    4914     .12       0  5003.9     .07       0
  5016.2     .12       0  5156.9     .07       0
Bank Sta=5003.9,5016.2
XS Rating Curve= 0 ,0
Exp/Cntr=0.3,0.1

Type RM Length L Ch R = 1 ,4326    ,456,456,456
BEGIN DESCRIPTION:
Bitter Creek Trib1 6.0
END DESCRIPTION:
XS GIS Cut Line= 3
      1422304.99      6790538.02      1422510.04      6790137.91
        1422505.      6789987.99
#Sta/Elev= 30
  4550.4 2450.51  4553.2 2450.51  4558.7 2448.78  4564.3 2448.95  4580.9 2446.48
  4653.1  2444.6  4669.7 2443.55  4780.7    2441  4808.9 2439.56  4825.1 2441.11
  4841.7 2438.64  4869.5 2437.38  4886.1 2435.16  4891.7 2435.43  4898.8 2434.38
  4921.2 2435.01  4942.3 2433.95  4966.2 2433.72  4990.9  2431.2  4991.4  2430.7
  5002.8  2430.7  5003.3  2431.2  5039.9 2432.69  5059.9 2435.52  5071.5 2438.12
    5090 2443.16    5110 2450.18    5120 2452.27    5130 2455.54    5150 2456.75
#Mann= 5 ,-1 , 0
  4550.4     .07       0  4942.3     .16       0  4990.9     .07       0
  5003.3     .16       0  5071.5     .12       0
Bank Sta=4990.9,5003.3
XS Rating Curve= 0 ,0
Exp/Cntr=0.3,0.1

Type RM Length L Ch R = 1 ,3870    ,581,581,581
BEGIN DESCRIPTION:
Bitter Creek Trib1 5.0
END DESCRIPTION:
XS GIS Cut Line= 3
      1422754.98      6790538.04      1422938.43      6790154.89
      1422704.99      6789837.99
#Sta/Elev= 30
  4575.2 2446.11  4597.4 2444.18  4619.6 2443.23  4741.5 2439.61  4763.7 2438.05
  4770.7 2436.25  4793.3 2435.02  4808.1 2436.31  4821.5  2435.5  4830.2 2436.05
  4844.2 2435.67  4874.6  2432.9  4934.9 2430.66  4941.1 2429.89  4976.5 2429.43
  4979.5 2429.31    4980 2428.81  4991.4 2428.81  4991.9 2429.31    5097 2432.62
    5121 2434.05    5144 2433.47    5215 2436.51  5244.3 2438.54  5250.5 2439.69
    5257 2442.03  5270.4 2444.48  5306.9 2450.84    5357 2457.01  5393.6 2460.57
#Mann= 6 ,-1 , 0
  4575.2     .07       0  4976.5     .12       0  4979.5     .07       0
  4991.9     .12       0    5097    .035       0  5270.4     .07       0
Bank Sta=4979.5,4991.9
XS Rating Curve= 0 ,0
Exp/Cntr=0.3,0.1