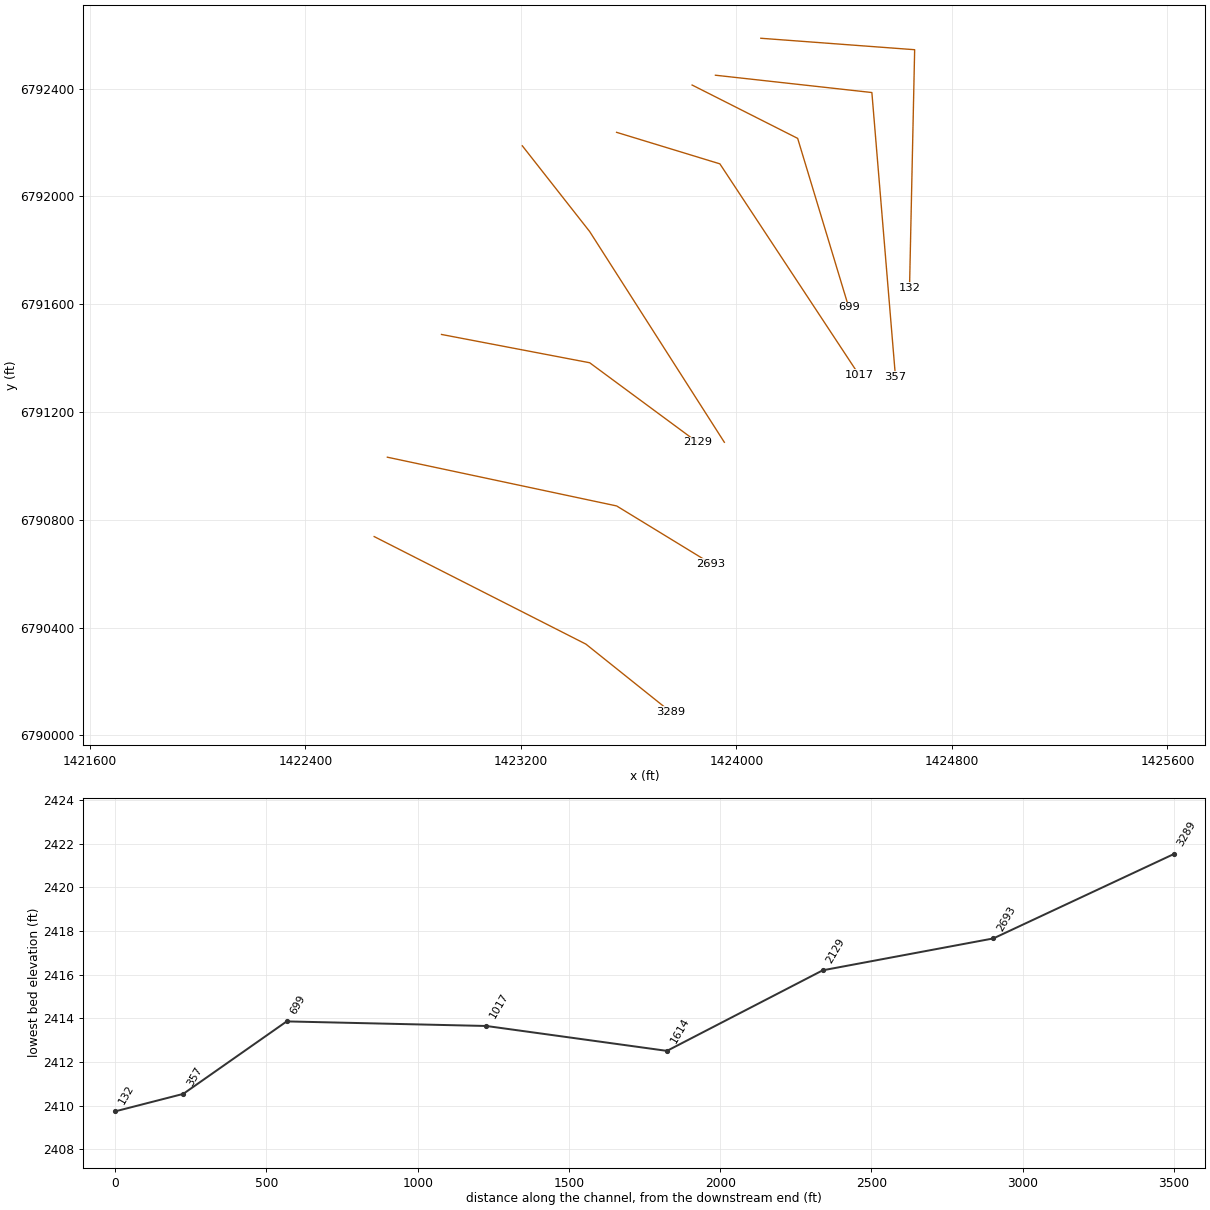
HEC-RAS study Bitter Creek Trib1.prj: Bitter Creek Trib1 Base Level Engineering

--- Bitter Creek Trib1.g01 (geometry) --- (continued)

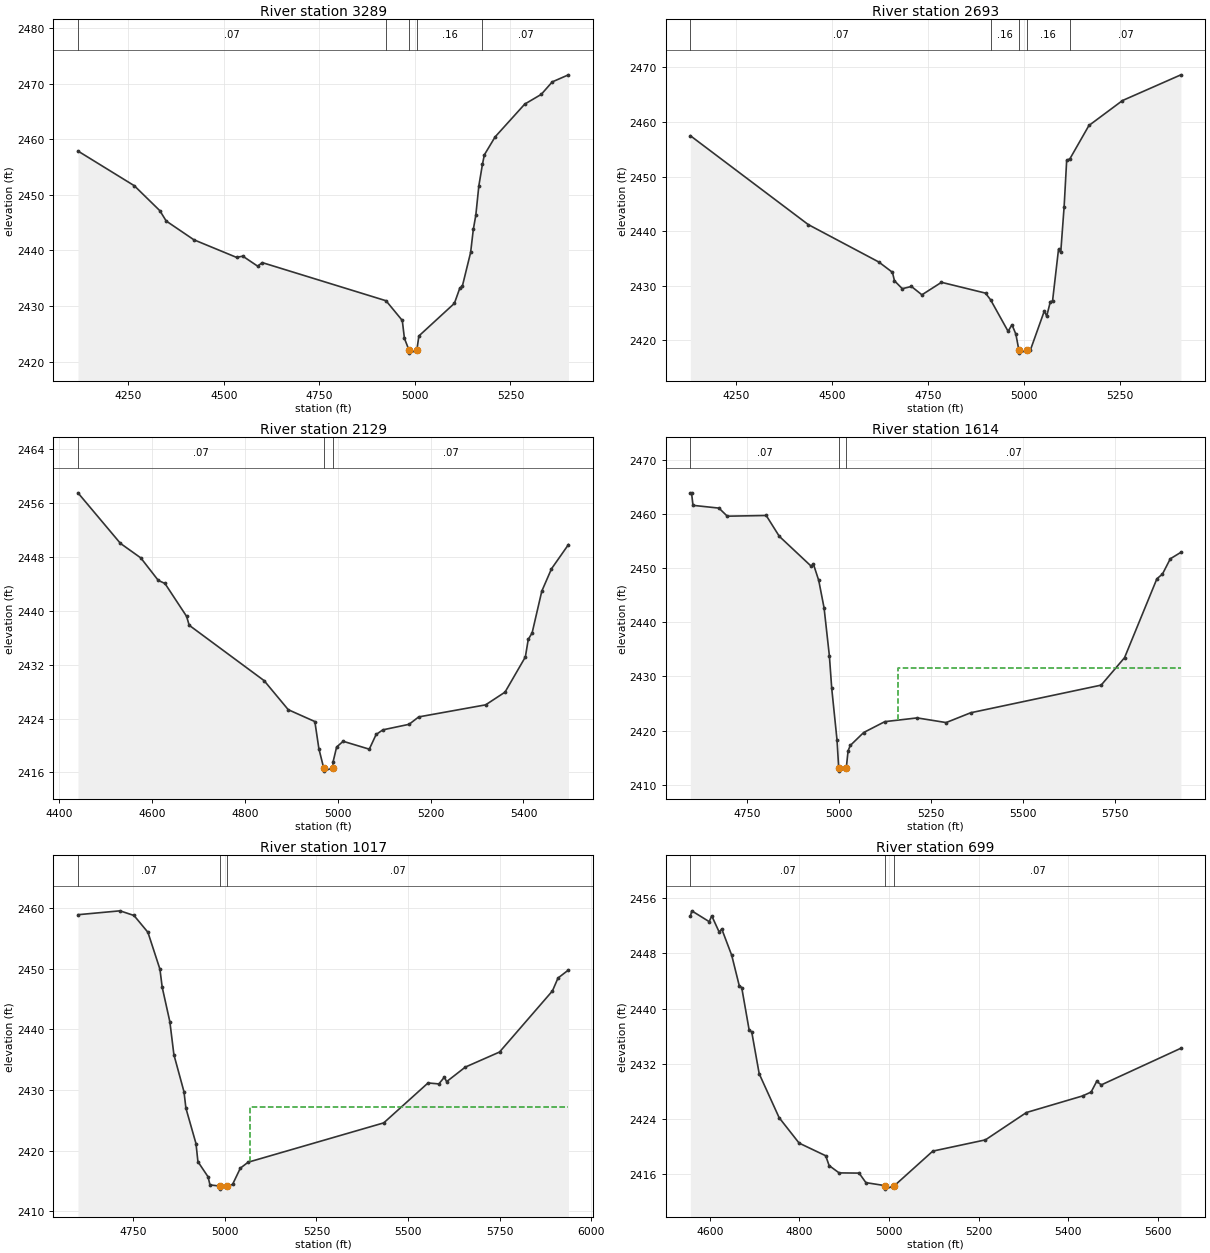
Type RM Length L Ch R = 1 ,3289    ,596,596,596
BEGIN DESCRIPTION:
Bitter Creek Trib1 4.0
END DESCRIPTION:
XS GIS Cut Line= 3
      1422655.02      6790737.99      1423440.95      6790339.01
      1423754.97      6790088.02
#Sta/Elev= 30
  4118.6 2457.91  4266.1 2451.66  4332.9 2447.17  4349.5 2445.31  4421.9 2441.93
  4533.5 2438.76  4549.9 2438.98  4588.8 2437.18  4600.8 2437.82  4924.7 2430.95
  4967.2  2427.4  4972.8 2424.18    4985 2422.02  4985.5 2421.52  5005.2 2422.02
  5010.6 2424.61  5103.5 2430.48  5117.9 2433.26  5124.3 2433.56    5146 2439.65
  5153.1 2443.83  5159.5 2446.31  5167.5 2451.64  5176.9 2455.51  5181.9 2457.22
    5210 2460.45  5287.6 2466.36  5330.8 2468.11  5359.6 2470.36    5402 2471.63
#Mann= 5 ,-1 , 0
  4118.6     .07       0  4924.7     .16       0    4985     .07       0
  5005.2     .16       0  5176.9     .07       0
Bank Sta=4985,5005.2
XS Rating Curve= 0 ,0
Exp/Cntr=0.3,0.1

Type RM Length L Ch R = 1 ,2693    ,564,564,564
BEGIN DESCRIPTION:
Bitter Creek Trib1 3.0
END DESCRIPTION:
XS GIS Cut Line= 3
      1422703.93      6791032.56      1423555.13      6790851.69
      1423905.03      6790637.98
#Sta/Elev= 30
  4129.8 2457.48  4437.6  2441.2  4621.6 2434.35  4657.2 2432.46  4662.5 2430.91
  4682.9 2429.46  4706.8 2429.87  4734.1 2428.34  4785.2 2430.63  4900.1 2428.65
  4913.4 2427.42    4959 2421.66  4969.2 2422.86  4979.4 2421.12  4987.3 2418.16
  4987.8 2417.66  5007.5 2418.16    5017 2418.18  5053.8 2425.42  5059.7 2424.41
  5069.3 2427.08  5075.1 2427.23  5090.6 2436.66  5096.4  2436.1  5105.3 2444.51
  5111.9 2452.94  5120.5 2453.27    5170 2459.35  5257.6 2463.92    5410 2468.63
#Mann= 5 ,-1 , 0
  4129.8     .07       0  4913.4     .16       0  4987.3     .07       0
  5007.5     .16       0  5120.5     .07       0
Bank Sta=4987.3,5007.5
XS Rating Curve= 0 ,0
Exp/Cntr=0.3,0.1

Type RM Length L Ch R = 1 ,2129    ,515,515,515
BEGIN DESCRIPTION:
Bitter Creek Trib1 2.0
END DESCRIPTION:
XS GIS Cut Line= 3
      1422904.99        6791488.      1423455.06      6791383.03
      1423855.01      6791087.99
#Sta/Elev= 30
    4440 2457.52  4531.6 2450.01  4575.4 2447.86  4613.1 2444.52  4627.5 2444.06
  4674.2 2439.17  4679.7 2437.86  4841.1 2429.64  4893.2 2425.32  4950.5 2423.56
  4959.2 2419.52  4969.4  2416.7  4969.9  2416.2  4989.7  2416.7  4989.8 2417.58
  4997.4 2419.78  5011.5 2420.63  5067.8 2419.46  5082.5 2421.64  5097.1 2422.33
  5153.5 2423.15  5174.3 2424.25  5318.5 2426.04  5360.3 2427.93  5404.1 2433.15
  5410.3 2435.75  5418.7 2436.73  5439.5 2442.92  5460.4 2446.24    5497 2449.84
#Mann= 3 ,-1 , 0
    4440     .07       0  4969.4     .07       0  4989.7     .07       0
Bank Sta=4969.4,4989.7
XS Rating Curve= 0 ,0
Exp/Cntr=0.3,0.1

Type RM Length L Ch R = 1 ,1614    ,597,597,597
BEGIN DESCRIPTION:
Bitter Creek Trib1 1.0
END DESCRIPTION:
XS GIS Cut Line= 3
      1423205.02      6792187.98      1423455.09      6791869.79
      1423955.02      6791087.96
#Sta/Elev= 30
  4595.3 2463.86  4598.5 2463.86  4602.5 2461.55    4673 2461.04  4695.6 2459.55
  4801.4 2459.68  4836.9 2455.84  4923.3 2450.34  4929.7 2450.69  4944.1 2447.69
  4958.6 2442.62    4973 2433.78  4979.4 2427.76  4993.8 2418.22  4998.4 2413.01
  4998.9 2412.51  5018.8 2413.01  5023.8 2416.24  5029.7 2417.24  5066.1 2419.63
  5123.6 2421.64  5211.6 2422.33  5290.2 2421.47    5357 2423.28  5711.4 2428.38
  5774.9 2433.44  5862.8    2448    5878 2448.88  5899.2 2451.69    5928 2452.88
#Mann= 3 ,-1 , 0
  4595.3     .07       0  4998.4     .07       0  5018.8     .07       0
#XS Ineff= 2 , 0
                         5158.58         2431.48
Permanent Ineff=
       F       F
Bank Sta=4998.4,5018.8
XS Rating Curve= 0 ,0
Exp/Cntr=0.3,0.1

Type RM Length L Ch R = 1 ,1017    ,660,660,660
BEGIN DESCRIPTION:
Bitter Creek Trib1 0.1
END DESCRIPTION:
XS GIS Cut Line= 3
      1423554.97      6792238.01      1423938.44      6792121.08
      1424454.99      6791338.01
#Sta/Elev= 30
  4599.1 2458.93    4714 2459.57  4752.1  2458.8  4790.1 2456.03  4822.9 2449.94
  4829.1 2446.96    4850 2441.27    4861 2435.84  4888.6 2429.71  4893.8 2427.01
  4921.4 2421.15  4926.6 2418.18  4954.2 2415.69  4959.5 2414.35  4986.5 2414.15
    4987 2413.65  5006.9 2414.15  5021.3 2414.44  5042.4 2417.11  5063.6 2418.09
  5433.8 2424.58  5554.8 2431.17  5584.3 2431.01  5599.4 2432.13  5605.4 2431.38
  5656.6 2433.79  5749.9 2436.27  5894.4 2446.36  5909.5 2448.48  5938.1 2449.81
#Mann= 3 ,-1 , 0
  4599.1     .07       0  4986.5     .07       0  5006.9     .07       0
#XS Ineff= 2 , 0
                         5069.24         2427.28
Permanent Ineff=
       F       F
Bank Sta=4986.5,5006.9
XS Rating Curve= 0 ,0
Exp/Cntr=0.3,0.1

Type RM Length L Ch R = 1 ,699     ,342,342,342
BEGIN DESCRIPTION:
Mapping XS 0c764e17
END DESCRIPTION:
XS GIS Cut Line= 3
      1423835.42       6792413.5      1424227.23      6792215.57
      1424417.08      6791588.13
#Sta/Elev= 30
  4556.8 2453.32  4559.9 2454.14  4598.9 2452.57  4604.5 2453.42  4621.2 2451.05
  4626.8 2451.52  4649.1  2447.7  4665.8 2443.33  4671.4 2443.03  4688.1 2436.85
  4693.7 2436.63  4710.4 2430.56  4754.9  2424.2  4799.5 2420.52  4858.8 2418.69
  4866.4 2417.27  4888.7 2416.21  4933.3 2416.18  4948.5  2414.8  4991.7 2414.36
  4992.2 2413.86  5012.1 2414.36  5097.7 2419.36  5215.2 2420.99  5306.7 2424.95
    5432 2427.35    5451 2427.91  5463.4 2429.45  5473.8 2428.95  5651.3 2434.25
#Mann= 3 ,-1 , 0
  4556.8     .07       0  4991.7     .07       0  5012.1     .07       0
Bank Sta=4991.7,5012.1
XS Rating Curve= 0 ,0
Exp/Cntr=0.3,0.1

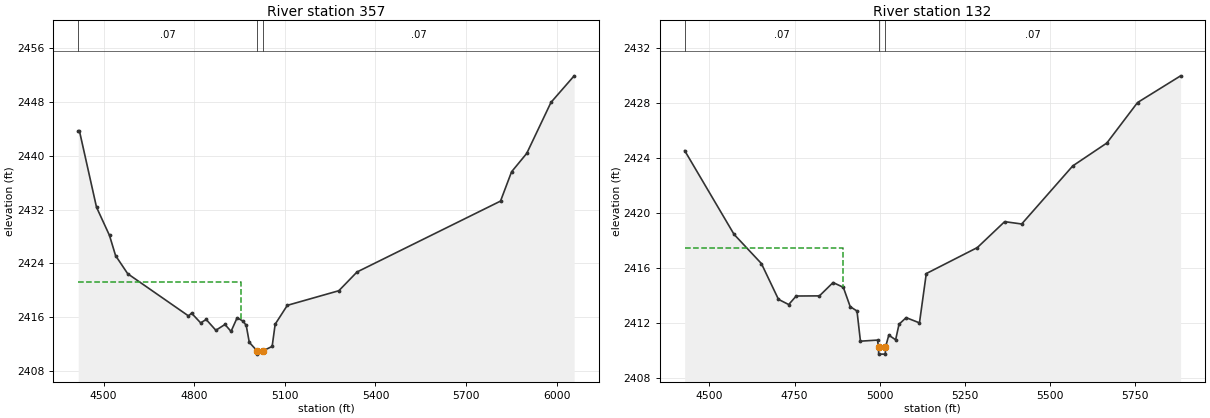
Type RM Length L Ch R = 1 ,357     ,225,225,225
BEGIN DESCRIPTION:
Bitter Creek Trib1 4464
END DESCRIPTION:
XS GIS Cut Line= 3
      1423922.07      6792449.92      1424502.73      6792385.71
      1424590.32      6791331.54
#Sta/Elev= 30
  4415.8 2443.67  4419.8 2443.67  4476.4 2432.34  4519.4 2428.15  4539.5 2425.16
  4579.7 2422.47  4780.9 2416.21    4791 2416.62  4821.2 2415.18  4839.5 2415.68
  4871.5 2414.08  4901.7 2414.94  4921.8 2413.91  4941.9 2415.93    4962 2415.43
  4972.1 2414.79  4982.2 2412.29  5007.6 2411.04  5008.1 2410.54    5028 2411.04
  5057.9 2411.68  5067.9 2414.98  5108.1 2417.78  5278.7 2419.95  5338.9 2422.73
    5814 2433.25  5850.6  2437.6  5900.8 2440.33  5981.1  2447.9  6057.8 2451.84
#Mann= 3 ,-1 , 0
  4415.8     .07       0  5007.6     .07       0    5028     .07       0
#XS Ineff= 2 , 0
         4953.71 2421.26
Permanent Ineff=
       F       F
Bank Sta=5007.6,5028
XS Rating Curve= 0 ,0
Exp/Cntr=0.3,0.1

Type RM Length L Ch R = 1 ,132     ,0,0,0
BEGIN DESCRIPTION:
Bitter Creek Trib1 4465
END DESCRIPTION:
XS GIS Cut Line= 3
      1424090.46      6792587.08      1424661.58      6792544.57
      1424642.55      6791661.48
#Sta/Elev= 30
  4427.3 2424.52  4572.2 2418.44  4652.5 2416.32  4702.6 2413.72  4732.7 2413.34
  4754.7 2413.96  4822.9 2413.97    4863 2414.94  4893.1 2414.59  4913.2 2413.19
  4933.2 2412.87  4943.3 2410.68  4993.4 2410.76  4996.4 2410.24  4996.9 2409.74
  5016.3 2409.74  5016.8 2410.24  5026.6 2411.12  5046.6 2410.78  5056.6 2411.91
  5077.5 2412.39  5116.6 2412.01  5136.6 2415.59  5286.6 2417.48  5366.7 2419.36
  5416.7 2419.19  5566.7 2423.41  5666.7 2425.07  5756.8 2428.01  5883.3 2429.95
#Mann= 3 ,-1 , 0
  4427.3     .07       0  4996.4     .07       0  5016.8     .07       0
#XS Ineff= 2 , 0
         4892.18 2417.44
Permanent Ineff=
       F       F
Bank Sta=4996.4,5016.8
XS Rating Curve= 0 ,0
Exp/Cntr=0.3,0.1

Chan Stop Cuts=-1
Use User Specified Reach Order=0
Composite Channel Slope=5