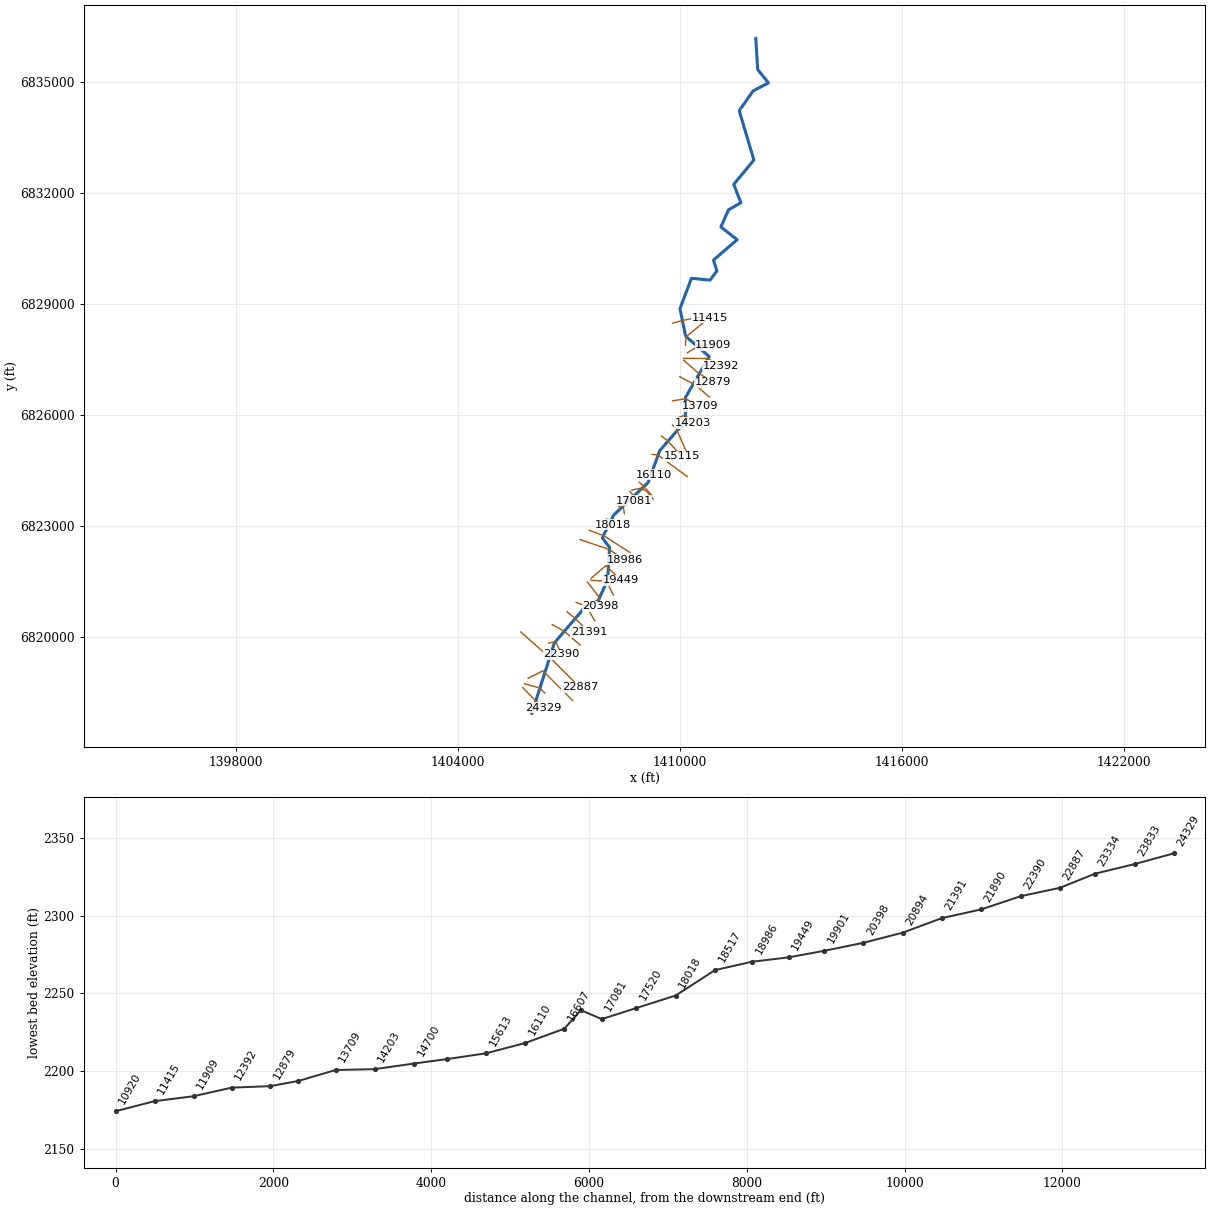
--- Bitter Creek Trib10.prj (project) ---

Proj Title=Bitter Creek Trib10 Base Level Engineering
Current Plan=p01
Default Exp/Contr=0.3,0.1
English Units
Geom File=g01
Flow File=f01
Plan File=p01
BEGIN DESCRIPTION:
Bitter Creek Trib10
END DESCRIPTION:

--- Bitter Creek Trib10.p01 (plan) ---

Plan Title=Multiple Run
Short Identifier=Multiple
Geom File=g01
Flow File=f01
Subcritical Flow
K Sum by GR= 0
Std Step Tol= 0.01
Critical Tol= 0.01
Num of Std Step Trials= 20
Max Error Tol= 0.3
Flow Tol Ratio= 0.001
Split Flow NTrial= 30
Split Flow Tol= 0.02
Split Flow Ratio= 0.02
Log Output Level= 0
Friction Slope Method= 1
Unsteady Friction Slope Method= 2
Unsteady Bridges Friction Slope Method= 1
Parabolic Critical Depth
Global Vel Dist=  1 , 1 , 1
Global Log Level= 0
CheckData=True
Encroach Param= -1, 0, 0, 0
BEGIN DESCRIPTION:
Multiple Run
END DESCRIPTION:

--- Bitter Creek Trib10.f01 (steady flow) ---

Flow Title=Multiple
Number of Profiles=7
Profile Names=10-year,25-year,50-year,1pct_min,100-year,1pct_plu,500-year
River Rch & RM= Bitter Creek Tri,Reach-1,24329
     496     732     938     598    1192    2379    1953
River Rch & RM= Bitter Creek Tri,Reach-1,18018
     585     869    1119     716    1428    2850    2360
River Rch & RM= Bitter Creek Tri,Reach-1,16817
     884    1336    1741    1126    2247    4483    3790
River Rch & RM= Bitter Creek Tri,Reach-1,9428
    1049    1594    2085    1351    2696    5380    4572
River Rch & RM= Bitter Creek Tri,Reach-1,4041
    1180    1798    2356    1529    3051    6088    5189
Boundary for River Rch & Prof#=Bitter Creek Tri,Reach-1,1
Up Type=0
Dn Type=3
Dn Slope=0.005
Boundary for River Rch & Prof#=Bitter Creek Tri,Reach-1,2
Up Type=0
Dn Type=3
Dn Slope=0.005
Boundary for River Rch & Prof#=Bitter Creek Tri,Reach-1,3
Up Type=0
Dn Type=3
Dn Slope=0.005
Boundary for River Rch & Prof#=Bitter Creek Tri,Reach-1,4
Up Type=0
Dn Type=3
Dn Slope=0.005
Boundary for River Rch & Prof#=Bitter Creek Tri,Reach-1,5
Up Type=0
Dn Type=3
Dn Slope=0.005
Boundary for River Rch & Prof#=Bitter Creek Tri,Reach-1,6
Up Type=0
Dn Type=3
Dn Slope=0.005
Boundary for River Rch & Prof#=Bitter Creek Tri,Reach-1,7
Up Type=0
Dn Type=3
Dn Slope=0.005

--- Bitter Creek Trib10.g01 (geometry) ---

Geom Title=Existing Conditions

River Reach=Bitter Creek Tri,Reach-1
Reach XY= 30
      1406005.00      6817938.00      1406610.35      6819840.73
      1407460.08      6820832.96      1407791.60      6820974.69
      1408051.46      6821539.46      1408104.48      6822424.14
      1407908.31      6822686.26      1408218.61      6823301.24
      1409147.15      6824181.81      1409460.56      6825040.36
      1410149.54      6825835.55      1410158.75      6826486.45
      1410797.23      6827584.59      1410160.28      6828135.29
      1410005.99      6828877.70      1410317.69      6829701.41
      1410818.57      6829650.98      1411003.95      6829898.44
      1410912.45      6830194.05      1411553.43      6830744.09
      1411111.99      6831088.22      1411318.22      6831551.67
      1411652.96      6831743.85      1411460.34      6832240.74
      1412004.04      6832898.40      1411607.24      6834232.07
      1411981.43      6834765.14      1412397.25      6834984.60
      1412107.24      6835343.93      1412055.00      6836188.00

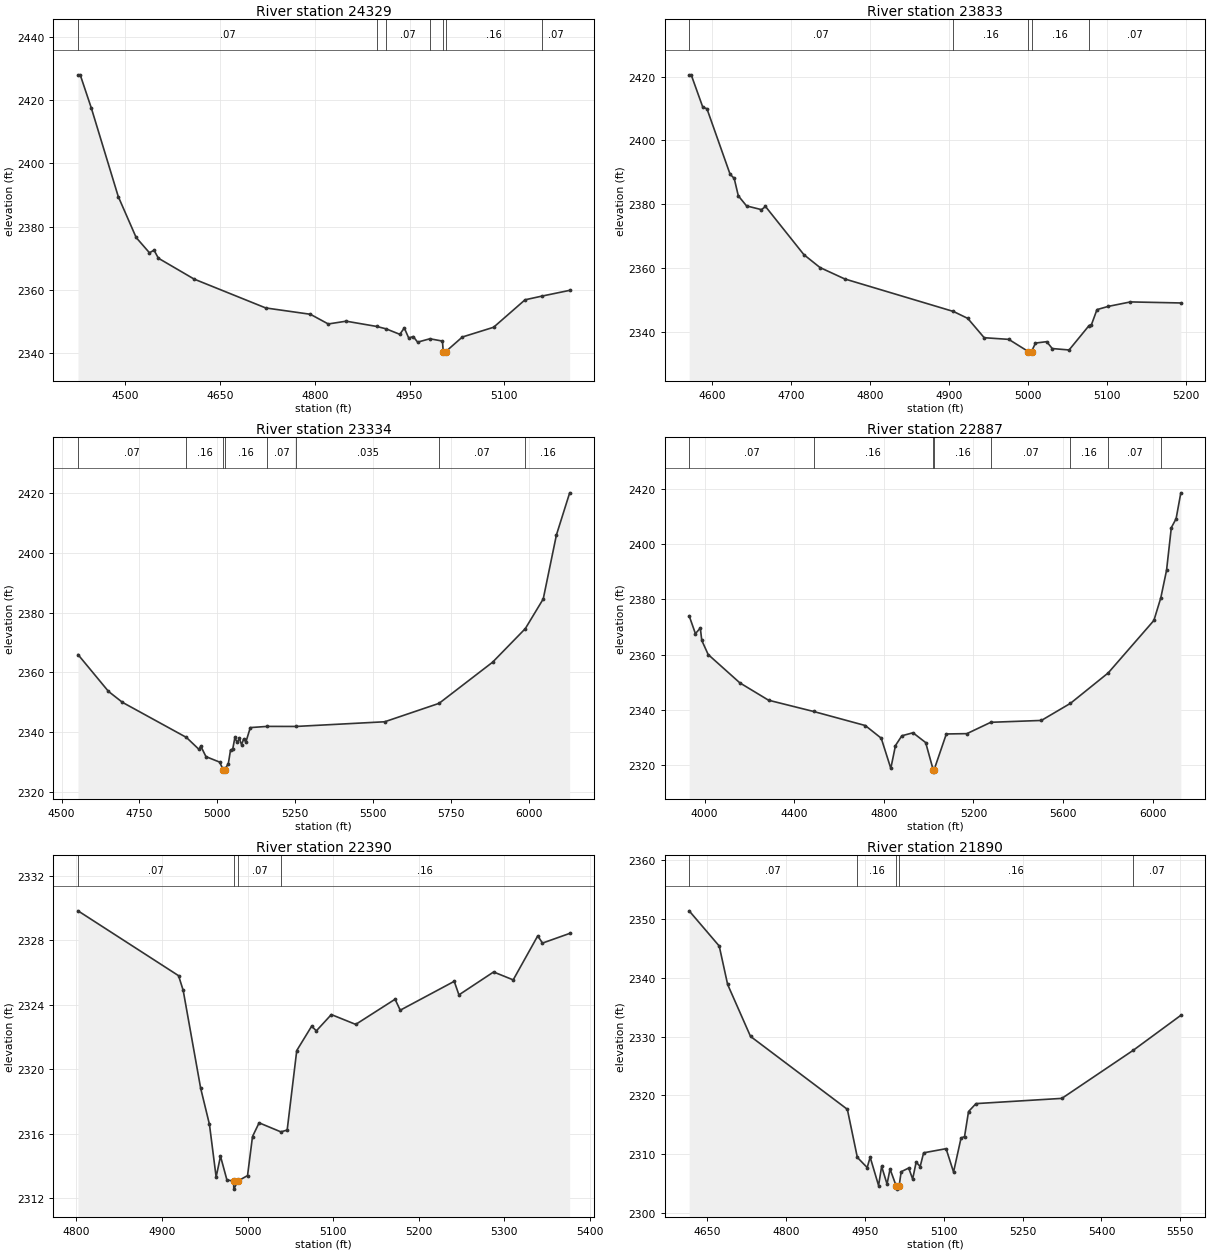
Type RM Length L Ch R = 1,24329,496,496,496
BEGIN DESCRIPTION:
Bitter Creek Trib10 42.0
END DESCRIPTION:
XS GIS Cut Line= 3
      1405754.98      6818638.02      1406156.88      6818227.36
      1406305.02      6818087.98
#Sta/Elev= 30
  4425.4 2427.92  4428.9 2427.92  4446.6 2417.37  4489.1 2389.51  4517.4 2376.59
  4538.5 2371.76  4545.7 2372.59  4552.6 2370.05  4609.2 2363.46  4722.4 2354.36
  4793.1 2352.36  4821.4 2349.30  4849.7 2350.18  4898.0 2348.52  4912.9 2347.76
  4934.6 2346.04  4941.7 2348.04  4948.7 2344.87  4955.8 2345.34  4962.8 2343.57
  4982.2 2344.63  5002.1 2343.90  5003.3 2340.60  5003.5 2340.10  5007.4 2340.60
  5033.6 2345.19  5083.0 2348.26  5132.8 2356.93  5159.6 2358.10  5203.4 2359.91
#Mann=7,-1,0
  4425.4    0.07       0  4898.0    0.16       0  4912.9    0.07       0
  4982.2    0.16       0  5003.3    0.07       0  5007.4    0.16       0
  5159.6    0.07       0
Bank Sta=5003.3,5007.4
Exp/Cntr=0.3,0.1

Type RM Length L Ch R = 1,23833,499,499,499
BEGIN DESCRIPTION:
Bitter Creek Trib10 41.0
END DESCRIPTION:
XS GIS Cut Line= 3
      1405804.97      6818738.01      1406218.86      6818624.78
      1406355.01      6818487.99
#Sta/Elev= 30
  4570.9 2420.60  4573.5 2420.60  4588.2 2410.42  4593.4 2409.96  4622.7 2389.39
  4627.9 2388.09  4633.1 2382.61  4643.5 2379.45  4662.4 2378.27  4667.5 2379.26
  4716.1 2364.13  4736.5 2360.09  4767.9 2356.50  4905.3 2346.30  4923.4 2344.13
  4944.2 2338.06  4975.3 2337.54  5000.0 2333.72  5000.3 2333.22  5004.1 2333.72
  5009.1 2336.38  5023.3 2336.82  5030.3 2334.66  5051.6 2334.21  5076.9 2341.88
  5079.9 2342.15  5086.9 2346.88  5101.1 2347.89  5129.3 2349.30  5193.0 2348.97
#Mann=5,-1,0
  4570.9    0.07       0  4905.3    0.16       0  5000.0    0.07       0
  5004.1    0.16       0  5076.9    0.07       0
Bank Sta=5000,5004.1
Exp/Cntr=0.3,0.1

Type RM Length L Ch R = 1,23334,447,447,447
BEGIN DESCRIPTION:
Bitter Creek Trib10 40.0
END DESCRIPTION:
XS GIS Cut Line= 3
      1405904.96      6818887.98      1406304.92      6819088.04
      1407105.03      6818287.97
#Sta/Elev= 30
  4552.8 2365.98  4650.7 2353.68  4695.4 2350.04  4901.0 2338.32  4941.3 2334.33
  4946.9 2335.43  4963.7 2331.91  5007.2 2330.11  5019.2 2327.58  5019.5 2327.08
  5023.3 2327.58  5035.4 2329.54  5042.5 2334.08  5049.6 2334.44  5056.6 2338.32
  5063.7 2336.64  5070.8 2337.98  5077.9 2335.89  5084.9 2337.85  5092.0 2336.85
  5106.1 2341.61  5161.0 2342.01  5252.9 2341.99  5537.5 2343.55  5712.1 2349.70
  5884.0 2363.43  5989.0 2374.63  6046.6 2384.54  6089.0 2405.92  6131.5 2419.95
#Mann=8,-1,0
  4552.8    0.07       0  4901.0    0.16       0  5019.2    0.07       0
  5023.3    0.16       0  5161.0    0.07       0  5252.9   0.035       0
  5712.1    0.07       0  5989.0    0.16       0
Bank Sta=5019.2,5023.3
Exp/Cntr=0.3,0.1

Type RM Length L Ch R = 1,22887,497,497,497
BEGIN DESCRIPTION:
Bitter Creek Trib10 39.0
END DESCRIPTION:
XS GIS Cut Line= 3
      1405705.02      6820137.98      1406507.36      6819432.02
      1407305.01      6818637.99
#Sta/Elev= 30
  3931.3 2374.09  3959.3 2367.64  3981.1 2369.67  3987.7 2365.19  4016.2 2360.09
  4157.7 2349.84  4285.6 2343.58  4486.5 2339.51  4717.3 2334.43  4788.5 2329.85
  4831.2 2318.95  4852.1 2327.21  4880.5 2330.73  4930.3 2331.81  4986.8 2328.27
  5020.3 2318.45  5020.6 2317.95  5024.5 2318.45  5079.0 2331.38  5170.9 2331.50
  5277.5 2335.60  5503.2 2336.27  5632.9 2342.45  5801.5 2353.45  6005.3 2372.41
  6036.1 2380.57  6061.8 2390.55  6083.1 2405.96  6104.3 2409.15  6125.5 2418.53
#Mann=8,-1,0
  3931.3    0.07       0  4486.5    0.16       0  5020.3    0.07       0
  5024.5    0.16       0  5277.5    0.07       0  5632.9    0.16       0
  5801.5    0.07       0  6036.1    0.16       0
Bank Sta=5020.3,5024.5
Exp/Cntr=0.3,0.1

Type RM Length L Ch R = 1,22390,500,500,500
BEGIN DESCRIPTION:
Bitter Creek Trib10 38.0
END DESCRIPTION:
XS GIS Cut Line= 3
      1406454.96      6819837.99      1406648.50      6819880.27
      1406805.02      6819537.96
#Sta/Elev= 30
  4801.9 2329.82  4919.4 2325.80  4924.8 2324.89  4945.2 2318.83  4955.5 2316.58
  4963.3 2313.32  4968.4 2314.61  4975.9 2313.14  4983.6 2313.07  4984.0 2312.57
  4988.7 2313.07  5000.0 2313.41  5005.8 2315.83  5013.5 2316.68  5038.9 2316.12
  5046.3 2316.23  5057.5 2321.16  5074.9 2322.67  5080.4 2322.38  5097.9 2323.39
  5126.4 2322.78  5172.4 2324.34  5178.4 2323.66  5241.5 2325.45  5247.0 2324.61
  5287.5 2326.03  5310.4 2325.54  5339.1 2328.27  5344.6 2327.82  5376.4 2328.42
#Mann=4,-1,0
  4801.9    0.07       0  4983.6    0.07       0  4988.7    0.07       0
  5038.9    0.16       0
Bank Sta=4983.6,4988.7
Exp/Cntr=0.3,0.1

Type RM Length L Ch R = 1,21890,499,499,499
BEGIN DESCRIPTION:
Bitter Creek Trib10 37.0
END DESCRIPTION:
XS GIS Cut Line= 3
      1406555.01      6820338.00      1406890.95      6820151.38
      1407305.01      6819787.99
#Sta/Elev= 30
  4615.7 2351.42  4672.9 2345.43  4688.9 2338.89  4732.4 2330.06  4916.6 2317.65
  4935.6 2309.47  4954.3 2307.74  4960.0 2309.50  4976.0 2304.68  4981.8 2307.94
  4992.1 2304.93  4997.8 2307.48  5009.7 2304.57  5010.2 2304.07  5015.0 2304.57
  5019.0 2307.03  5033.3 2307.66  5040.8 2305.79  5047.5 2308.67  5055.1 2307.91
  5061.7 2310.25  5104.4 2310.95  5118.6 2306.98  5132.9 2312.78  5139.5 2313.00
  5147.1 2317.27  5161.3 2318.62  5324.6 2319.51  5460.8 2327.72  5550.9 2333.64
#Mann=5,-1,0
  4615.7    0.07       0  4935.6    0.16       0  5009.7    0.07       0
  5015.0    0.16       0  5460.8    0.07       0
Bank Sta=5009.7,5015
Exp/Cntr=0.3,0.1

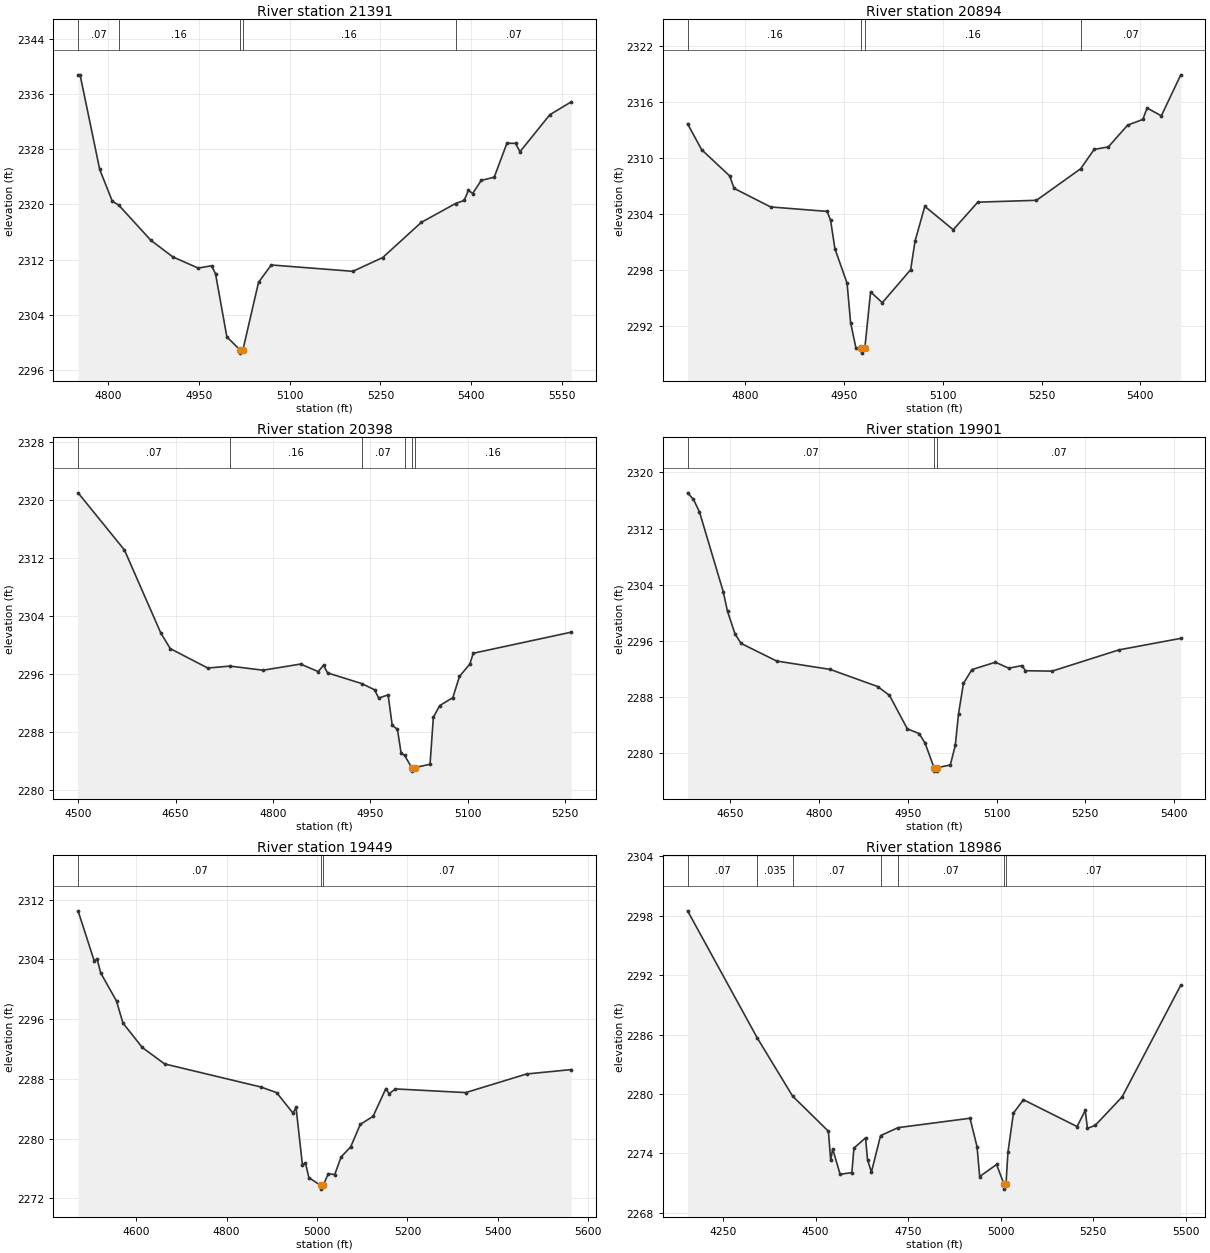
Type RM Length L Ch R = 1,21391,497,497,497
BEGIN DESCRIPTION:
Bitter Creek Trib10 36.0
END DESCRIPTION:
XS GIS Cut Line= 3
      1406955.02      6820687.99      1407145.30      6820527.23
      1407554.99      6820138.01
#Sta/Elev= 30
  4750.9 2338.77  4754.2 2338.77  4786.6 2325.07  4807.4 2320.46  4818.1 2319.89
  4871.2 2314.79  4907.5 2312.39  4949.2 2310.78  4971.2 2311.11  4977.8 2309.97
  4996.5 2300.82  5017.8 2298.96  5018.2 2298.46  5023.1 2298.96  5048.8 2308.71
  5069.8 2311.23  5204.5 2310.31  5253.9 2312.31  5317.4 2317.39  5374.0 2320.13
  5388.2 2320.57  5395.4 2322.04  5402.3 2321.58  5416.5 2323.48  5437.9 2323.94
  5458.9 2328.87  5473.1 2328.84  5480.4 2327.63  5529.7 2332.99  5565.1 2334.86
#Mann=5,-1,0
  4750.9    0.07       0  4818.1    0.16       0  5017.8    0.07       0
  5023.1    0.16       0  5374.0    0.07       0
Bank Sta=5017.8,5023.1
Exp/Cntr=0.3,0.1

Type RM Length L Ch R = 1,20894,496,496,496
BEGIN DESCRIPTION:
Bitter Creek Trib10 35.0
END DESCRIPTION:
XS GIS Cut Line= 3
      1407204.98      6820938.01      1407474.97      6820838.04
      1407705.02      6820437.97
#Sta/Elev= 30
  4712.1 2313.66  4733.4 2310.89  4776.1 2308.07  4782.8 2306.74  4838.2 2304.75
  4924.1 2304.27  4929.4 2303.33  4936.0 2300.27  4954.5 2296.57  4959.8 2292.37
  4968.0 2289.62  4976.0 2289.59  4976.5 2289.09  4981.4 2289.59  4990.2 2295.65
  5008.0 2294.49  5051.1 2298.03  5057.7 2301.08  5072.6 2304.81  5115.8 2302.31
  5153.1 2305.26  5242.3 2305.46  5309.4 2308.84  5329.9 2310.91  5351.5 2311.18
  5380.7 2313.51  5403.8 2314.12  5410.4 2315.34  5432.0 2314.51  5461.5 2318.90
#Mann=4,-1,0
  4712.1    0.16       0  4976.0    0.07       0  4981.4    0.16       0
  5309.4    0.07       0
Bank Sta=4976,4981.4
Exp/Cntr=0.3,0.1

Type RM Length L Ch R = 1,20398,497,497,497
BEGIN DESCRIPTION:
Bitter Creek Trib10 34.0
END DESCRIPTION:
XS GIS Cut Line= 3
      1407505.00      6821488.01      1407813.19      6821094.03
      1407855.00      6820838.02
#Sta/Elev= 30
  4499.8 2320.99  4571.2 2313.11  4627.3 2301.64  4641.8 2299.50  4699.6 2296.82
  4733.6 2297.09  4784.7 2296.52  4842.5 2297.37  4869.7 2296.33  4877.8 2297.21
  4884.1 2296.15  4936.9 2294.67  4956.4 2293.82  4962.8 2292.68  4977.3 2293.12
  4983.6 2288.94  4991.7 2288.36  4997.4 2285.04  5002.6 2284.79  5013.5 2283.10
  5014.0 2282.60  5018.9 2283.10  5041.9 2283.55  5047.0 2290.02  5056.8 2291.64
  5077.0 2292.74  5087.2 2295.66  5103.3 2297.39  5108.4 2298.86  5259.4 2301.77
#Mann=6,-1,0
  4499.8    0.07       0  4733.6    0.16       0  4936.9    0.07       0
  5002.6    0.16       0  5013.5    0.07       0  5018.9    0.16       0
Bank Sta=5013.5,5018.9
Exp/Cntr=0.3,0.1

Type RM Length L Ch R = 1,19901,452,452,452
BEGIN DESCRIPTION:
Bitter Creek Trib10 33.0
END DESCRIPTION:
XS GIS Cut Line= 3
      1407604.98      6821538.00      1408025.49      6821507.80
      1408205.02      6821137.97
#Sta/Elev= 30
  4578.4 2317.09  4588.4 2316.15  4598.5 2314.37  4638.6 2303.01  4645.9 2300.18
  4658.6 2296.97  4668.7 2295.63  4728.8 2293.12  4819.0 2291.93  4899.2 2289.49
  4919.3 2288.23  4949.4 2283.46  4969.4 2282.78  4979.5 2281.41  4994.5 2277.93
  4995.0 2277.43  4999.5 2277.43  4999.9 2277.93  5022.0 2278.30  5030.4 2281.09
  5035.9 2285.61  5044.2 2289.94  5058.5 2291.90  5098.1 2292.95  5120.7 2292.10
  5143.2 2292.47  5148.8 2291.74  5193.9 2291.68  5306.7 2294.71  5411.1 2296.35
#Mann=3,-1,0
  4578.4    0.07       0  4994.5    0.07       0  4999.9    0.07       0
Bank Sta=4994.5,4999.9
Exp/Cntr=0.3,0.1

Type RM Length L Ch R = 1,19449,463,463,463
BEGIN DESCRIPTION:
Bitter Creek Trib10 32.0
END DESCRIPTION:
XS GIS Cut Line= 3
      1407605.02      6821588.02      1408004.91      6821933.42
      1408404.99      6821538.01
#Sta/Elev= 30
  4471.6 2310.49  4507.2 2303.80  4513.8 2304.03  4521.5 2302.19  4556.6 2298.41
  4570.8 2295.47  4613.6 2292.19  4663.0 2289.99  4875.8 2286.90  4910.9 2286.14
  4947.1 2283.39  4953.7 2284.18  4967.9 2276.44  4974.5 2276.75  4982.2 2274.75
  5008.3 2273.72  5008.7 2273.22  5013.7 2273.72  5025.1 2275.29  5039.3 2275.17
  5053.4 2277.53  5074.6 2278.88  5095.8 2281.89  5124.1 2282.97  5152.4 2286.68
  5159.4 2285.99  5173.6 2286.64  5329.2 2286.15  5463.6 2288.64  5562.5 2289.23
#Mann=3,-1,0
  4471.6    0.07       0  5008.3    0.07       0  5013.7    0.07       0
Bank Sta=5008.3,5013.7
Exp/Cntr=0.3,0.1

Type RM Length L Ch R = 1,18986,469,469,469
BEGIN DESCRIPTION:
Bitter Creek Trib10 31.0
END DESCRIPTION:
XS GIS Cut Line= 3
      1407305.00      6822638.00      1408105.42      6822365.29
      1408505.02      6822087.98
#Sta/Elev= 30
  4154.4 2298.51  4342.5 2285.68  4438.0 2279.80  4534.7 2276.25  4541.0 2273.30
  4546.3 2274.47  4566.4 2271.90  4598.1 2272.07  4603.7 2274.54  4635.1 2275.58
  4640.4 2273.37  4650.9 2272.12  4675.6 2275.80  4722.8 2276.61  4917.2 2277.56
  4936.2 2274.69  4943.3 2271.67  4989.0 2272.89  5009.0 2270.90  5009.4 2270.40
  5014.4 2270.90  5019.7 2274.14  5034.5 2278.08  5061.5 2279.43  5206.4 2276.72
  5228.4 2278.35  5234.4 2276.54  5255.4 2276.84  5328.1 2279.72  5486.4 2291.00
#Mann=7,-1,0
  4154.4    0.07       0  4342.5   0.035       0  4438.0    0.07       0
  4675.6    0.16       0  4722.8    0.07       0  5009.0    0.07       0
  5014.4    0.07       0
Bank Sta=5009,5014.4
Exp/Cntr=0.3,0.1

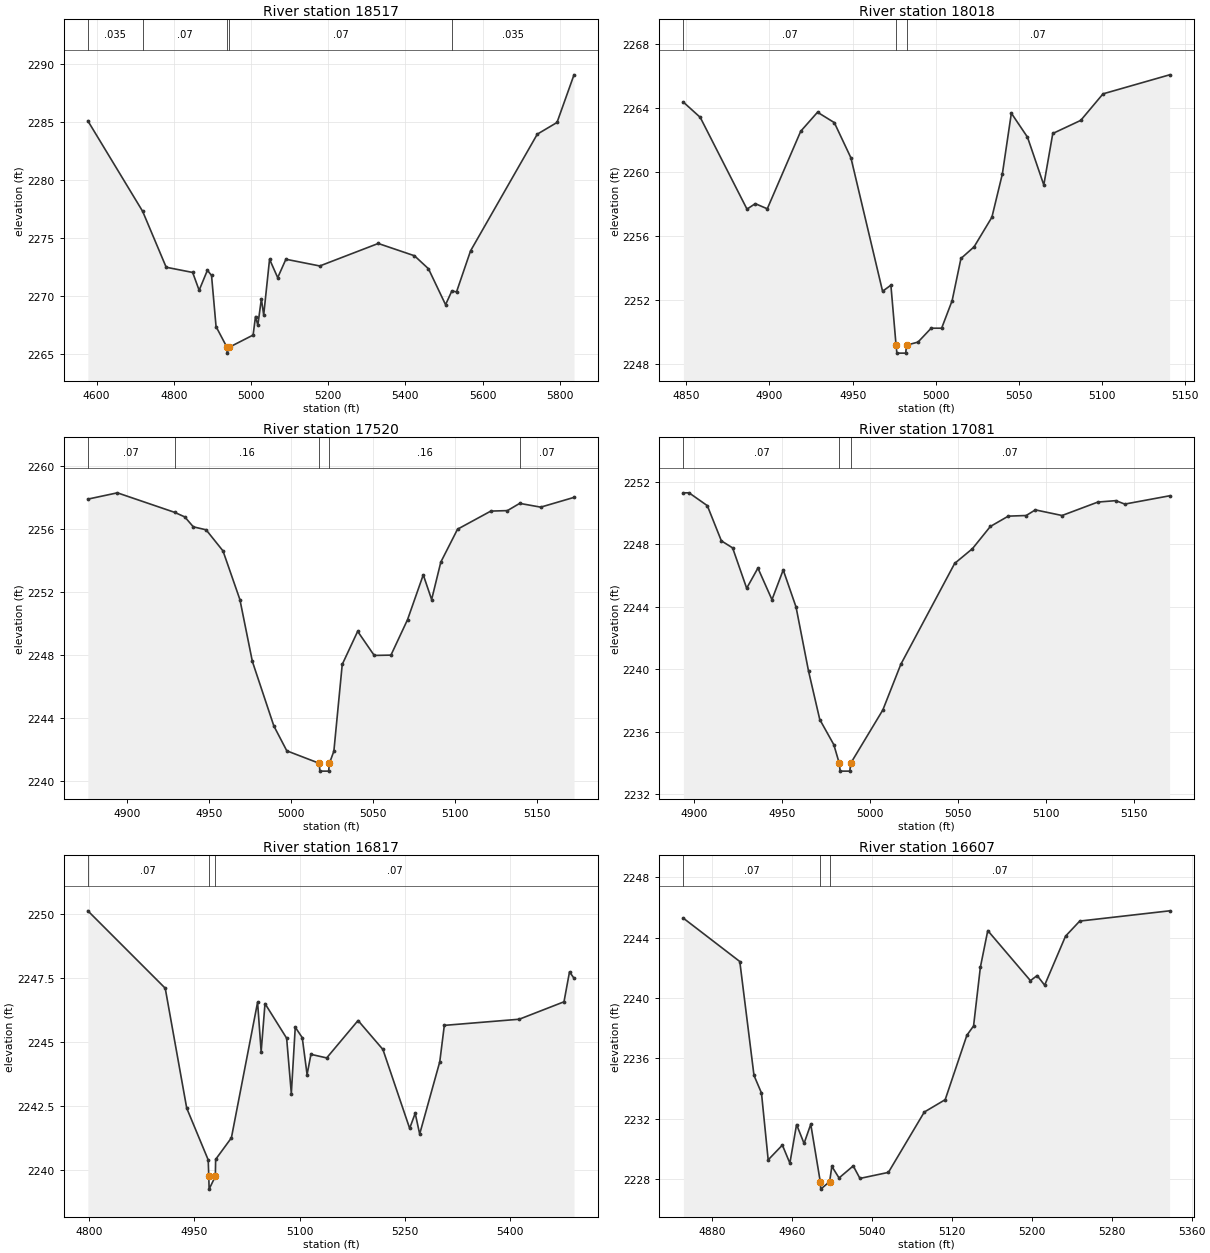
Type RM Length L Ch R = 1,18517,499,499,499
BEGIN DESCRIPTION:
Bitter Creek Trib10 30.0
END DESCRIPTION:
XS GIS Cut Line= 3
      1407555.01      6822888.00      1407950.75      6822739.73
      1408655.02      6822287.99
#Sta/Elev= 30
  4577.4 2285.08  4719.4 2277.27  4780.3 2272.45  4848.9 2272.00  4865.7 2270.46
  4887.1 2272.19  4897.8 2271.74  4909.5 2267.33  4937.8 2265.54  4938.2 2265.04
  4943.2 2265.54  5005.5 2266.60  5011.7 2268.20  5017.7 2267.45  5026.9 2269.72
  5032.9 2268.33  5048.1 2273.14  5069.2 2271.55  5090.4 2273.14  5178.2 2272.56
  5329.6 2274.50  5423.4 2273.44  5459.7 2272.32  5504.0 2269.22  5520.4 2270.41
  5532.4 2270.32  5568.7 2273.86  5741.6 2283.93  5792.7 2284.94  5836.7 2289.05
#Mann=5,-1,0
  4577.4   0.035       0  4719.4    0.07       0  4937.8    0.07       0
  4943.2    0.07       0  5520.4   0.035       0
Bank Sta=4937.8,4943.2
Exp/Cntr=0.3,0.1

Type RM Length L Ch R = 1,18018,498,498,498
BEGIN DESCRIPTION:
Bitter Creek Trib10 29.0
END DESCRIPTION:
XS GIS Cut Line= 3
      1408005.01      6823188.00      1408155.59      6823169.57
      1408204.98      6823038.04
#Sta/Elev= 30
  4848.3 2264.37  4858.4 2263.42  4886.5 2257.68  4891.5 2258.02  4898.7 2257.70
  4918.8 2262.55  4928.9 2263.74  4939.0 2263.09  4949.0 2260.88  4968.0 2252.54
  4973.0 2252.92  4976.1 2249.17  4976.6 2248.67  4981.9 2248.67  4982.4 2249.17
  4989.3 2249.36  4997.2 2250.23  5003.5 2250.23  5009.8 2251.95  5015.1 2254.59
  5023.0 2255.32  5033.7 2257.17  5040.0 2259.88  5045.4 2263.68  5055.1 2262.18
  5064.9 2259.19  5070.3 2262.41  5087.1 2263.23  5100.5 2264.89  5140.5 2266.08
#Mann=3,-1,0
  4848.3    0.07       0  4976.1    0.07       0  4982.4    0.07       0
Bank Sta=4976.1,4982.4
Exp/Cntr=0.3,0.1

Type RM Length L Ch R = 1,17520,439,439,439
BEGIN DESCRIPTION:
Bitter Creek Trib10 28.0
END DESCRIPTION:
XS GIS Cut Line= 3
      1408355.05      6823537.99      1408475.41      6823507.77
      1408505.00      6823338.03
#Sta/Elev= 30
  4875.9 2257.90  4893.9 2258.30  4928.8 2257.06  4935.0 2256.77  4940.2 2256.14
  4948.0 2255.95  4958.3 2254.61  4968.6 2251.52  4976.2 2247.59  4989.3 2243.49
  4997.2 2241.91  5016.9 2241.12  5017.4 2240.62  5022.7 2240.62  5023.2 2241.12
  5025.9 2241.89  5031.0 2247.40  5040.4 2249.50  5050.5 2247.97  5060.7 2247.99
  5070.8 2250.24  5080.4 2253.09  5085.5 2251.52  5091.1 2253.90  5101.3 2255.99
  5121.6 2257.14  5131.7 2257.17  5139.2 2257.63  5152.0 2257.39  5172.3 2258.01
#Mann=5,-1,0
  4875.9    0.07       0  4928.8    0.16       0  5016.9    0.07       0
  5023.2    0.16       0  5139.2    0.07       0
Bank Sta=5016.9,5023.2
Exp/Cntr=0.3,0.1

Type RM Length L Ch R = 1,17081,264,264,264
BEGIN DESCRIPTION:
Bitter Creek Trib10 27.0
END DESCRIPTION:
XS GIS Cut Line= 3
      1408655.02      6823937.98      1408721.51      6823855.04
      1408755.01      6823687.97
#Sta/Elev= 30
  4893.7 2251.28  4896.9 2251.28  4907.3 2250.46  4915.3 2248.21  4921.7 2247.76
  4929.7 2245.18  4936.1 2246.47  4944.1 2244.45  4950.5 2246.35  4957.8 2243.98
  4964.9 2239.89  4971.3 2236.79  4979.3 2235.18  4982.4 2233.99  4982.9 2233.49
  4988.4 2233.49  4988.9 2233.99  5007.2 2237.40  5017.4 2240.31  5048.1 2246.77
  5058.2 2247.71  5068.4 2249.13  5078.6 2249.79  5088.8 2249.83  5094.0 2250.19
  5109.2 2249.83  5129.6 2250.69  5139.8 2250.78  5144.9 2250.56  5170.4 2251.09
#Mann=3,-1,0
  4893.7    0.07       0  4982.4    0.07       0  4988.9    0.07       0
Bank Sta=4982.4,4988.9
Exp/Cntr=0.3,0.1

Type RM Length L Ch R = 1,16817,210,210,210
BEGIN DESCRIPTION:
Bitter Creek Trib10 4459
END DESCRIPTION:
XS GIS Cut Line= 5
      1408707.21      6823974.15      1408904.62      6824018.36
      1408979.38      6824009.31      1409106.17      6823946.48
      1409280.30      6823733.39
#Sta/Elev= 30
  4797.7 2250.12  4908.2 2247.10  4938.9 2242.42  4969.6 2240.40  4970.4 2239.76
  4970.9 2239.26  4979.8 2239.76  4980.2 2240.42  5002.7 2241.26  5040.1 2246.55
  5045.2 2244.62  5050.7 2246.50  5081.6 2245.15  5088.3 2242.99  5093.9 2245.58
  5103.9 2245.17  5110.8 2243.73  5116.3 2244.52  5138.8 2244.38  5183.6 2245.84
  5219.1 2244.71  5257.3 2241.63  5265.2 2242.22  5271.6 2241.41  5300.3 2244.23
  5306.8 2245.65  5413.8 2245.89  5477.7 2246.57  5485.6 2247.74  5492.0 2247.49
#Mann=3,-1,0
  4797.7    0.07       0  4970.4    0.07       0  4979.8    0.07       0
Bank Sta=4970.4,4979.8
Exp/Cntr=0.3,0.1

Type RM Length L Ch R = 1,16607,497,497,497
BEGIN DESCRIPTION:
Bitter Creek Trib10 26.0
END DESCRIPTION:
XS GIS Cut Line= 3
      1408905.03      6824187.98      1409015.64      6824088.89
      1409240.57      6823836.73
#Sta/Elev= 30
  4851.5 2245.28  4907.9 2242.41  4922.1 2234.86  4929.6 2233.69  4936.3 2229.26
  4950.5 2230.24  4958.0 2229.04  4964.7 2231.60  4972.2 2230.35  4978.9 2231.62
  4988.4 2227.82  4988.9 2227.32  4997.8 2227.82  5000.0 2228.83  5007.2 2228.06
  5021.4 2228.86  5028.1 2228.03  5056.6 2228.43  5092.5 2232.43  5113.4 2233.25
  5135.1 2237.52  5141.8 2238.14  5148.6 2242.03  5156.0 2244.46  5198.7 2241.14
  5205.4 2241.48  5212.9 2240.84  5233.8 2244.09  5248.0 2245.09  5337.9 2245.77
#Mann=3,-1,0
  4851.5    0.07       0  4988.4    0.07       0  4997.8    0.07       0
Bank Sta=4988.4,4997.8
Exp/Cntr=0.3,0.1

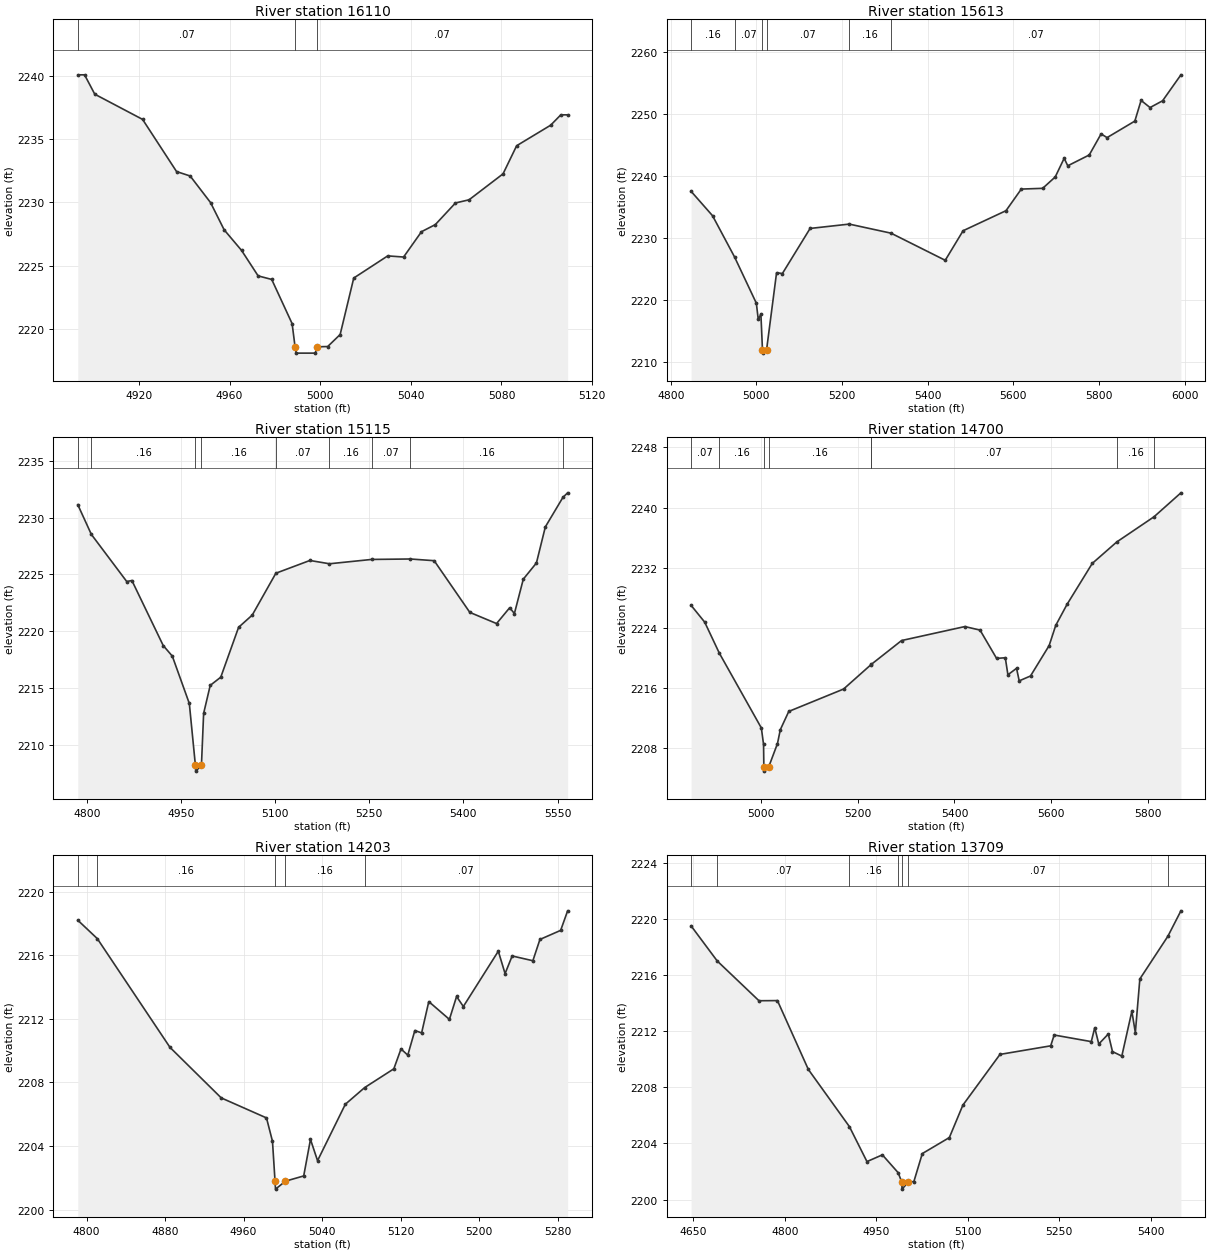
Type RM Length L Ch R = 1,16110,497,497,497
BEGIN DESCRIPTION:
Bitter Creek Trib10 25.0
END DESCRIPTION:
XS GIS Cut Line= 3
      1409154.97      6824538.02      1409243.86      6824478.47
      1409305.01      6824387.99
#Sta/Elev= 30
  4893.0 2240.07  4896.0 2240.07  4900.5 2238.54  4921.6 2236.55  4936.6 2232.43
  4942.6 2232.08  4951.6 2229.98  4957.6 2227.83  4965.3 2226.20  4972.6 2224.19
  4978.6 2223.91  4987.6 2220.42  4988.9 2218.59  4989.4 2218.09  4997.9 2218.09
  4998.4 2218.59  5003.3 2218.61  5008.8 2219.56  5014.8 2224.02  5029.8 2225.77
  5036.8 2225.68  5044.7 2227.68  5050.8 2228.24  5059.7 2229.95  5065.7 2230.20
  5080.7 2232.25  5086.7 2234.47  5101.7 2236.09  5106.2 2236.91  5109.2 2236.91
#Mann=3,-1,0
  4893.0    0.07       0  4988.9    0.07       0  4998.4    0.07       0
Bank Sta=4988.9,4998.4
Exp/Cntr=0.3,0.1

Type RM Length L Ch R = 1,15613,498,498,498
BEGIN DESCRIPTION:
Bitter Creek Trib10 24.0
END DESCRIPTION:
XS GIS Cut Line= 3
      1409255.05      6824938.00      1409406.98      6824926.03
      1410205.02      6824337.98
#Sta/Elev= 30
  4847.6 2237.53  4897.7 2233.60  4949.0 2226.97  5000.0 2219.51  5004.4 2216.90
  5010.6 2217.75  5014.3 2211.97  5014.8 2211.47  5023.8 2211.97  5047.2 2224.42
  5060.8 2224.29  5125.5 2231.55  5216.9 2232.25  5314.4 2230.79  5441.0 2226.42
  5482.7 2231.18  5582.9 2234.41  5618.6 2237.89  5668.5 2238.01  5697.8 2239.84
  5718.7 2242.85  5727.1 2241.64  5777.2 2243.38  5804.9 2246.77  5818.9 2246.18
  5883.7 2248.84  5898.3 2252.17  5919.2 2251.02  5948.5 2252.11  5991.3 2256.29
#Mann=6,-1,0
  4847.6    0.16       0  4949.0    0.07       0  5014.3    0.07       0
  5023.8    0.07       0  5216.9    0.16       0  5314.4    0.07       0
Bank Sta=5014.3,5023.8
Exp/Cntr=0.3,0.1

Type RM Length L Ch R = 1,15115,415,415,415
BEGIN DESCRIPTION:
Bitter Creek Trib10 23.0
END DESCRIPTION:
XS GIS Cut Line= 3
      1409505.01      6825437.99      1409675.38      6825307.84
      1410054.99      6824888.01
#Sta/Elev= 30
  4785.6 2231.13  4807.2 2228.52  4863.6 2224.38  4871.8 2224.47  4921.7 2218.76
  4936.2 2217.83  4963.3 2213.67  4973.0 2208.23  4973.5 2207.73  4982.6 2208.23
  4986.1 2212.80  4996.6 2215.26  5013.4 2215.98  5041.8 2220.36  5063.5 2221.43
  5101.2 2225.11  5155.4 2226.23  5186.6 2225.94  5253.7 2226.32  5315.4 2226.36
  5353.4 2226.21  5410.2 2221.67  5452.8 2220.69  5473.7 2222.08  5481.2 2221.57
  5495.4 2224.59  5516.3 2226.01  5530.5 2229.18  5558.5 2231.77  5566.0 2232.17
#Mann=9,-1,0
  4785.6    0.07       0  4807.2    0.16       0  4973.0    0.07       0
  4982.6    0.16       0  5101.2    0.07       0  5186.6    0.16       0
  5253.7    0.07       0  5315.4    0.16       0  5558.5    0.07       0
Bank Sta=4973,4982.6
Exp/Cntr=0.3,0.1

Type RM Length L Ch R = 1,14700,497,497,497
BEGIN DESCRIPTION:
Bitter Creek Trib10 22.0
END DESCRIPTION:
XS GIS Cut Line= 3
      1409804.99      6825738.01      1409906.77      6825634.03
      1410255.01      6824837.97
#Sta/Elev= 30
  4854.5 2226.98  4882.7 2224.74  4913.0 2220.61  5000.0 2210.65  5004.6 2208.45
  5005.2 2205.40  5005.7 2204.90  5014.9 2205.40  5033.4 2208.57  5039.3 2210.42
  5056.8 2212.85  5170.3 2215.83  5226.6 2219.05  5227.6 2219.11  5290.4 2222.29
  5421.4 2224.15  5452.9 2223.68  5487.2 2219.91  5505.2 2220.00  5510.6 2217.73
  5528.5 2218.59  5534.0 2216.92  5557.4 2217.57  5596.0 2221.62  5609.6 2224.30
  5633.0 2227.10  5685.3 2232.56  5736.1 2235.42  5813.2 2238.77  5868.9 2241.96
#Mann=8,-1,0
  4854.5    0.07       0  4913.0    0.16       0  5005.2    0.07       0
  5014.9    0.16       0  5226.6    0.16       0  5227.6    0.07       0
  5736.1    0.16       0  5813.2    0.07       0
Bank Sta=5005.2,5014.9
Exp/Cntr=0.3,0.1

Type RM Length L Ch R = 1,14203,494,494,494
BEGIN DESCRIPTION:
Bitter Creek Trib10 21.0
END DESCRIPTION:
XS GIS Cut Line= 3
      1409955.03      6825938.01      1410155.12      6825998.05
      1410355.03      6825787.96
#Sta/Elev= 30
  4791.1 2218.21  4811.0 2217.05  4885.0 2210.21  4937.2 2207.03  4983.3 2205.77
  4989.4 2204.30  4992.0 2201.79  4992.5 2201.29  5002.6 2201.79  5021.2 2202.12
  5028.1 2204.42  5035.3 2203.08  5063.6 2206.63  5083.3 2207.68  5113.0 2208.86
  5120.3 2210.11  5127.2 2209.72  5134.4 2211.27  5141.3 2211.12  5148.6 2213.09
  5169.6 2211.97  5176.9 2213.41  5183.8 2212.78  5219.4 2216.26  5226.3 2214.85
  5233.5 2215.96  5254.6 2215.66  5261.8 2217.00  5282.9 2217.57  5290.0 2218.80
#Mann=5,-1,0
  4791.1    0.07       0  4811.0    0.16       0  4992.0    0.07       0
  5002.6    0.16       0  5083.3    0.07       0
Bank Sta=4992,5002.6
Exp/Cntr=0.3,0.1

Type RM Length L Ch R = 1,13709,474,474,474
BEGIN DESCRIPTION:
Bitter Creek Trib10 20.0
END DESCRIPTION:
XS GIS Cut Line= 3
      1409804.99      6826388.00      1410154.56      6826443.18
      1410554.96      6826238.02
#Sta/Elev= 30
  4646.1 2219.49  4689.0 2216.99  4757.5 2214.16  4787.8 2214.17  4838.5 2209.27
  4905.9 2205.20  4934.7 2202.71  4960.0 2203.19  4985.9 2201.92  4991.8 2201.25
  4992.3 2200.75  5002.5 2201.25  5011.7 2201.29  5025.5 2203.28  5069.9 2204.42
  5092.1 2206.73  5153.0 2210.34  5236.2 2210.95  5241.9 2211.72  5302.8 2211.25
  5308.5 2212.24  5315.1 2211.08  5330.7 2211.79  5337.6 2210.54  5352.9 2210.22
  5369.4 2213.41  5375.1 2211.89  5382.5 2215.71  5428.5 2218.75  5449.9 2220.56
#Mann=7,-1,0
  4646.1    0.16       0  4689.0    0.07       0  4905.9    0.16       0
  4985.9    0.07       0  4991.8    0.07       0  5002.5    0.07       0
  5428.5    0.16       0
Bank Sta=4991.8,5002.5
Exp/Cntr=0.3,0.1

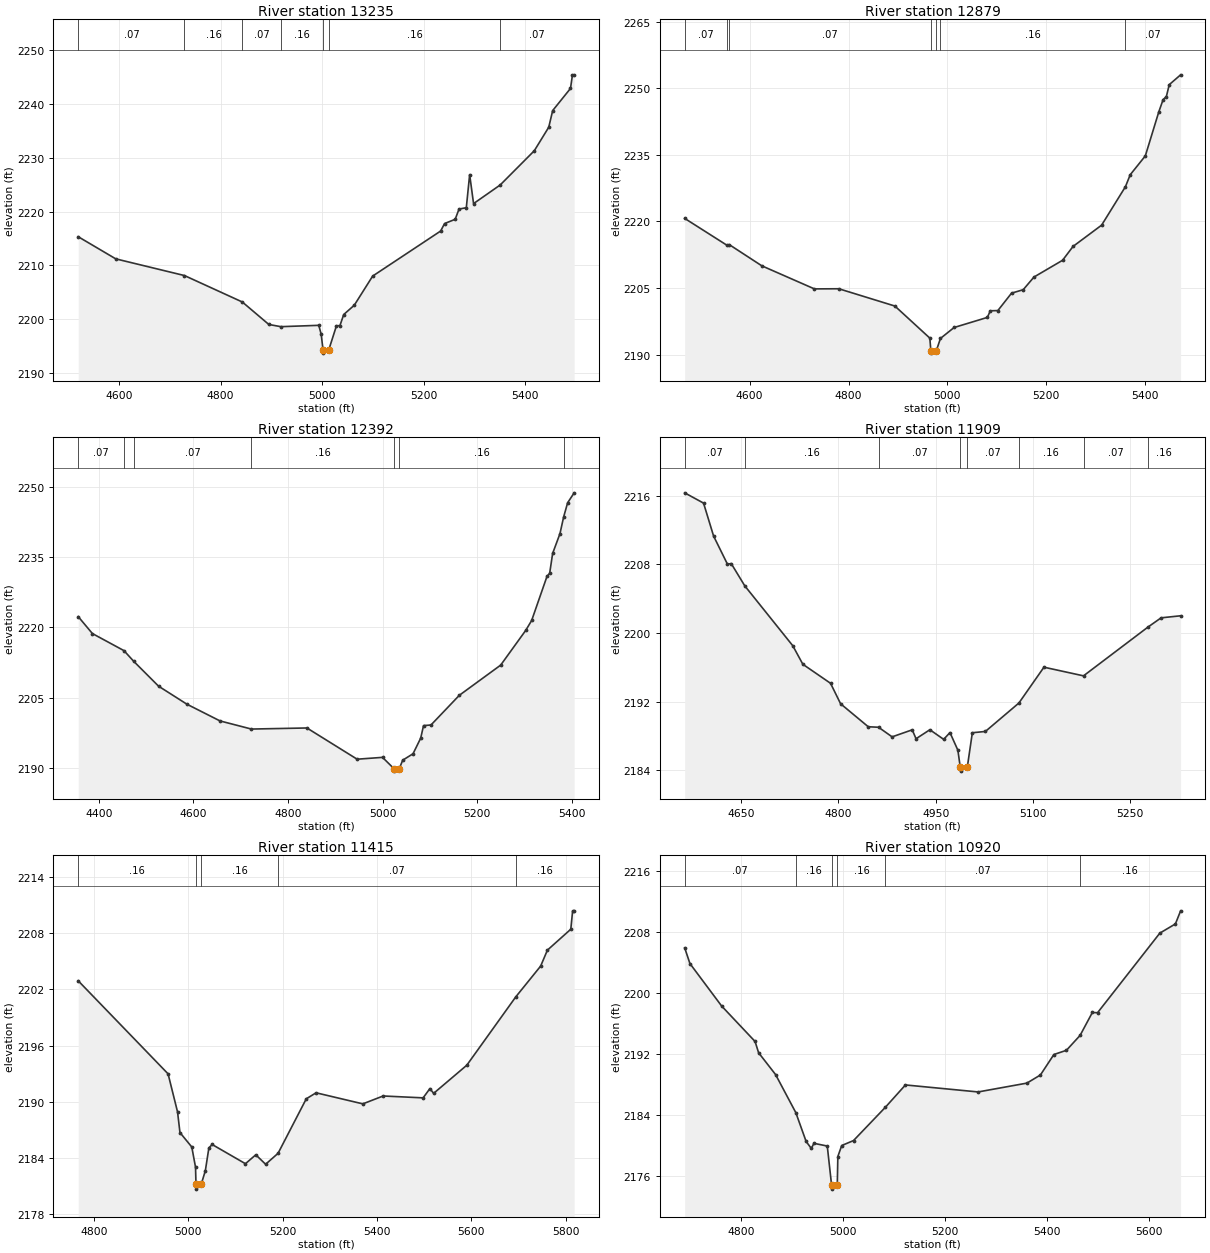
Type RM Length L Ch R = 1,13235,356,356,356
BEGIN DESCRIPTION:
Bitter Creek Trib10 19.0
END DESCRIPTION:
XS GIS Cut Line= 3
      1410004.96      6827038.02      1410428.39      6826811.31
      1410805.04      6826487.97
#Sta/Elev= 30
  4519.7 2215.32  4593.7 2211.20  4728.9 2208.10  4842.9 2203.18  4895.1 2199.00
  4918.8 2198.59  4993.5 2198.84  4998.2 2197.18  5002.0 2194.17  5002.5 2193.67
  5012.8 2194.17  5028.3 2198.76  5035.1 2198.78  5042.6 2200.85  5063.4 2202.58
  5099.6 2208.00  5233.5 2216.38  5241.2 2217.77  5262.1 2218.56  5269.7 2220.47
  5284.0 2220.71  5290.6 2226.87  5298.3 2221.48  5350.7 2224.94  5417.9 2231.31
  5446.4 2235.69  5454.1 2238.78  5489.2 2242.90  5493.1 2245.43  5496.4 2245.43
#Mann=7,-1,0
  4519.7    0.07       0  4728.9    0.16       0  4842.9    0.07       0
  4918.8    0.16       0  5002.0    0.07       0  5012.8    0.16       0
  5350.7    0.07       0
Bank Sta=5002,5012.8
Exp/Cntr=0.3,0.1

Type RM Length L Ch R = 1,12879,487,487,487
BEGIN DESCRIPTION:
Bitter Creek Trib10 18.0
END DESCRIPTION:
XS GIS Cut Line= 3
      1410105.02      6827487.98      1410504.92      6827138.03
      1410905.02      6826887.99
#Sta/Elev= 30
  4468.6 2220.69  4553.6 2214.68  4558.9 2214.78  4624.7 2210.01  4731.0 2204.82
  4780.4 2204.85  4893.8 2200.96  4964.5 2193.74  4966.6 2190.86  4967.1 2190.36
  4977.5 2190.86  4986.0 2193.67  5013.6 2196.13  5080.9 2198.40  5086.8 2199.89
  5102.1 2199.94  5129.8 2203.86  5153.4 2204.64  5175.2 2207.49  5233.0 2211.26
  5254.2 2214.38  5312.0 2219.17  5360.2 2227.83  5369.8 2230.51  5400.4 2234.76
  5427.6 2244.65  5436.4 2247.44  5442.9 2248.09  5448.8 2250.80  5471.8 2253.01
#Mann=7,-1,0
  4468.6    0.07       0  4553.6    0.16       0  4558.9    0.07       0
  4966.6    0.07       0  4977.5    0.07       0  4986.0    0.16       0
  5360.2    0.07       0
Bank Sta=4966.6,4977.5
Exp/Cntr=0.3,0.1

Type RM Length L Ch R = 1,12392,483,483,483
BEGIN DESCRIPTION:
Bitter Creek Trib10 17.0
END DESCRIPTION:
XS GIS Cut Line= 3
      1410105.01      6827538.00      1410748.68      6827531.33
      1411105.01      6827338.00
#Sta/Elev= 30
  4356.3 2222.31  4386.3 2218.70  4453.1 2215.06  4473.8 2212.78  4526.3 2207.49
  4586.3 2203.65  4656.3 2200.09  4722.7 2198.36  4840.1 2198.59  4946.3 2191.94
  5000.0 2192.33  5024.5 2189.90  5025.0 2189.40  5035.4 2189.90  5042.7 2191.73
  5064.6 2193.10  5080.8 2196.43  5086.8 2199.09  5102.6 2199.23  5162.5 2205.55
  5250.0 2211.98  5303.0 2219.38  5315.5 2221.48  5347.9 2230.86  5353.6 2231.53
  5359.9 2235.77  5375.4 2239.98  5383.2 2243.54  5391.6 2246.55  5405.4 2248.67
#Mann=7,-1,0
  4356.3    0.07       0  4453.1    0.16       0  4473.8    0.07       0
  4722.7    0.16       0  5024.5    0.07       0  5035.4    0.16       0
  5383.2    0.07       0
Bank Sta=5024.5,5035.4
Exp/Cntr=0.3,0.1

Type RM Length L Ch R = 1,11909,494,494,494
BEGIN DESCRIPTION:
Bitter Creek Trib10 16.0
END DESCRIPTION:
XS GIS Cut Line= 3
      1410204.97      6827687.98      1410578.41      6827914.75
      1410905.02      6827888.00
#Sta/Elev= 30
  4563.1 2216.36  4592.2 2215.16  4607.7 2211.31  4629.0 2208.04  4634.9 2208.10
  4655.7 2205.51  4729.8 2198.51  4745.3 2196.35  4788.0 2194.13  4803.5 2191.74
  4846.1 2189.06  4862.0 2189.00  4882.9 2187.88  4913.9 2188.70  4919.8 2187.66
  4941.1 2188.71  4962.4 2187.59  4972.1 2188.38  4984.3 2186.32  4987.9 2184.38
  4988.4 2183.88  4998.9 2184.38  5006.6 2188.36  5026.7 2188.51  5078.4 2191.83
  5117.0 2196.01  5178.0 2195.00  5277.5 2200.70  5297.6 2201.77  5327.7 2202.01
#Mann=8,-1,0
  4563.1    0.07       0  4655.7    0.16       0  4862.0    0.07       0
  4987.9    0.07       0  4998.9    0.07       0  5078.4    0.16       0
  5178.0    0.07       0  5277.5    0.16       0
Bank Sta=4987.9,4998.9
Exp/Cntr=0.3,0.1

Type RM Length L Ch R = 1,11415,495,495,495
BEGIN DESCRIPTION:
Bitter Creek Trib10 15.0
END DESCRIPTION:
XS GIS Cut Line= 3
      1410155.00      6827887.96      1410171.21      6828120.79
      1410804.97      6828637.98
#Sta/Elev= 30
  4766.6 2202.91  4957.1 2192.99  4977.2 2188.93  4982.3 2186.73  5007.4 2185.19
  5015.3 2183.04  5016.3 2181.20  5016.8 2180.70  5027.3 2181.20  5036.1 2182.66
  5043.6 2185.09  5050.5 2185.46  5121.1 2183.41  5143.1 2184.36  5163.9 2183.35
  5190.3 2184.52  5250.1 2190.33  5270.9 2190.97  5370.0 2189.79  5413.1 2190.63
  5497.8 2190.43  5512.2 2191.42  5520.1 2190.91  5590.4 2193.91  5694.3 2201.20
  5747.0 2204.48  5761.3 2206.18  5810.9 2208.41  5814.8 2210.37  5818.0 2210.37
#Mann=5,-1,0
  4766.6    0.16       0  5016.3    0.07       0  5027.3    0.16       0
  5190.3    0.07       0  5694.3    0.16       0
Bank Sta=5016.3,5027.3
Exp/Cntr=0.3,0.1

Type RM Length L Ch R = 1,10920,497,497,497
BEGIN DESCRIPTION:
Bitter Creek Trib10 14.0
END DESCRIPTION:
XS GIS Cut Line= 3
      1409805.04      6828488.01      1410104.54      6828567.64
      1410755.00      6828688.00
#Sta/Elev= 30
  4690.1 2205.93  4700.4 2203.86  4762.5 2198.28  4828.0 2193.62  4834.9 2192.14
  4868.2 2189.27  4907.8 2184.27  4928.0 2180.48  4938.1 2179.57  4943.3 2180.24
  4969.4 2179.88  4977.9 2174.72  4978.4 2174.22  4989.0 2174.72  4990.1 2178.50
  4997.7 2179.95  5020.8 2180.60  5083.4 2184.99  5122.5 2187.91  5264.9 2186.99
  5360.4 2188.15  5386.9 2189.22  5413.3 2191.91  5437.8 2192.46  5464.6 2194.42
  5488.6 2197.43  5498.8 2197.40  5620.8 2207.86  5651.3 2209.07  5661.5 2210.79
#Mann=6,-1,0
  4690.1    0.07       0  4907.8    0.16       0  4977.9    0.07       0
  4989.0    0.16       0  5083.4    0.07       0  5464.6    0.16       0
Bank Sta=4977.9,4989
Exp/Cntr=0.3,0.1