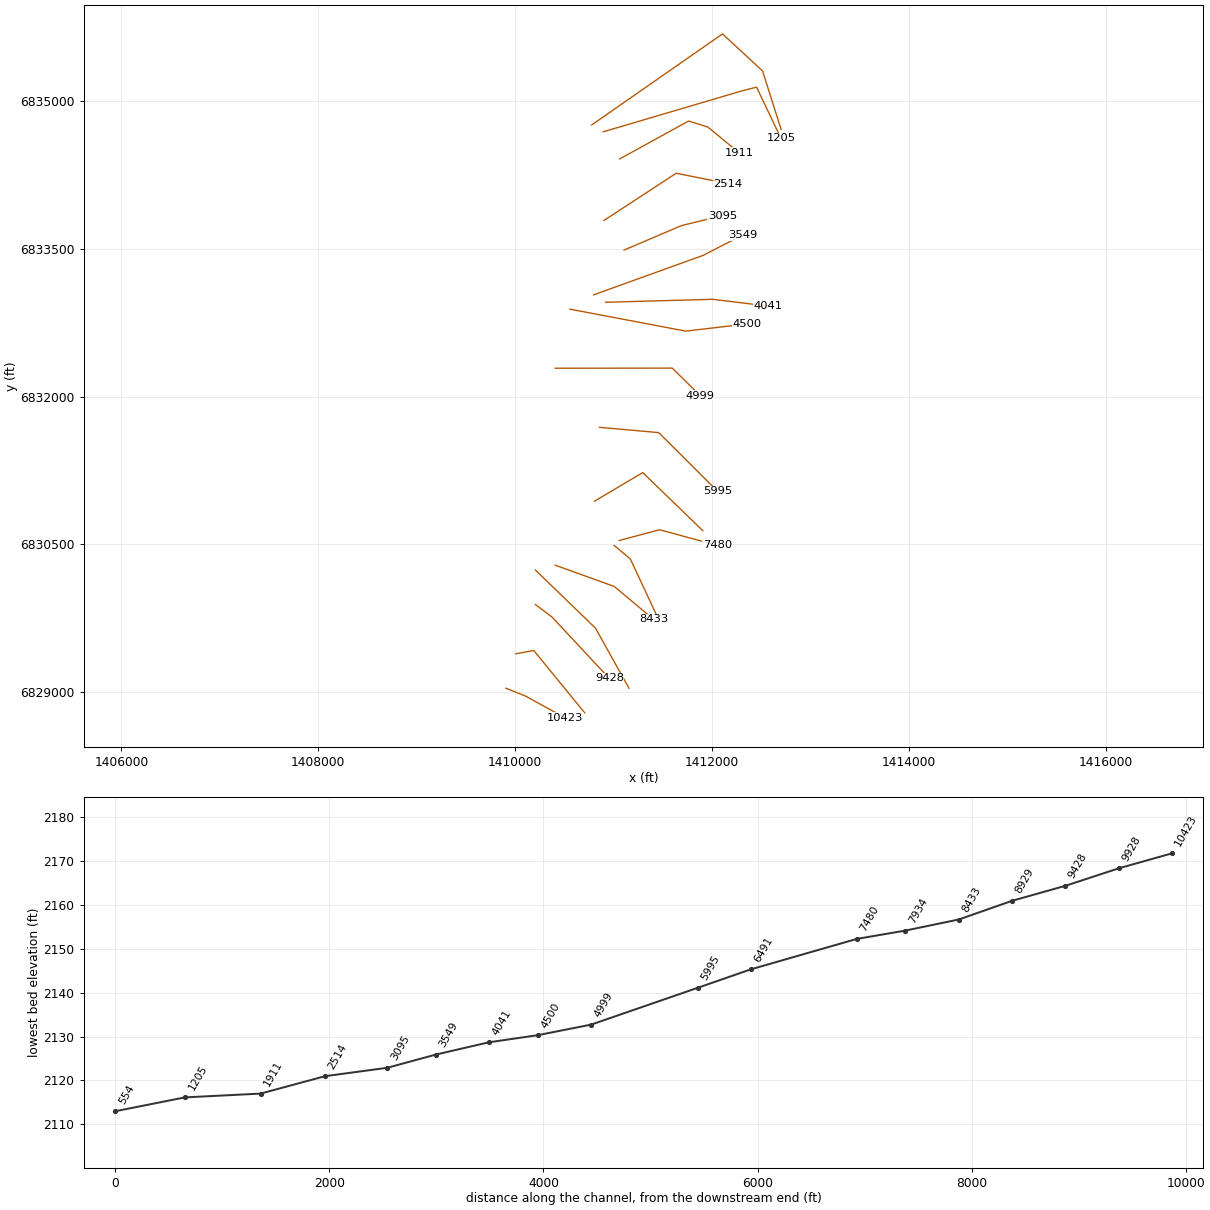
HEC-RAS study Bitter Creek Trib10.prj: Bitter Creek Trib10 Base Level Engineering

--- Bitter Creek Trib10.g01 (geometry) --- (continued)

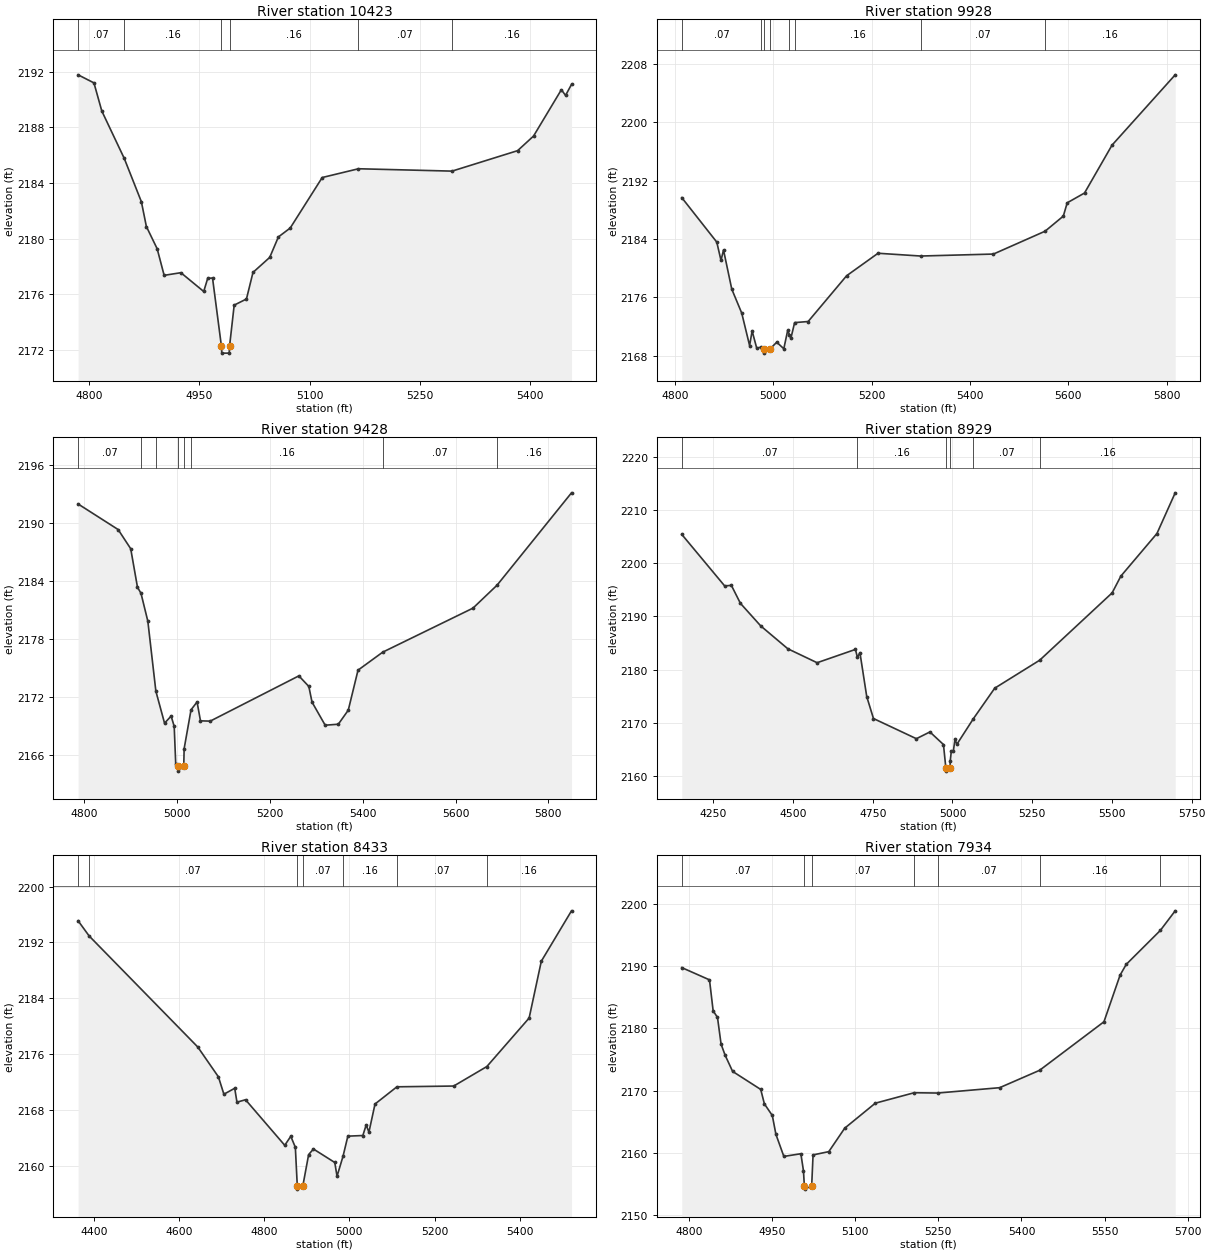
Type RM Length L Ch R = 1,10423,495,495,495
BEGIN DESCRIPTION:
Bitter Creek Trib10 13.0
END DESCRIPTION:
XS GIS Cut Line= 3
      1409904.98      6829038.01      1410104.94      6828958.20
      1410505.04      6828737.98
#Sta/Elev= 30
  4784.7 2191.78  4806.3 2191.20  4817.0 2189.18  4847.6 2185.77  4870.9 2182.66
  4877.7 2180.88  4892.4 2179.28  4901.9 2177.37  4924.7 2177.56  4955.8 2176.21
  4961.2 2177.15  4967.8 2177.18  4979.9 2172.28  4980.4 2171.78  4990.5 2171.78
  4991.0 2172.28  4997.3 2175.23  5014.0 2175.67  5022.9 2177.58  5045.7 2178.66
  5057.5 2180.13  5073.6 2180.77  5117.2 2184.40  5166.6 2185.03  5294.0 2184.86
  5383.3 2186.33  5405.0 2187.38  5442.9 2190.71  5448.6 2190.30  5456.7 2191.09
#Mann=6,-1,0
  4784.7    0.07       0  4847.6    0.16       0  4979.9    0.07       0
  4991.0    0.16       0  5166.6    0.07       0  5294.0    0.16       0
Bank Sta=4979.9,4991
Exp/Cntr=0.3,0.1

Type RM Length L Ch R = 1,9928,500,500,500
BEGIN DESCRIPTION:
Bitter Creek Trib10 12.0
END DESCRIPTION:
XS GIS Cut Line= 3
      1410004.96      6829387.99      1410188.21      6829421.56
      1410705.00      6828788.00
#Sta/Elev= 30
  4813.7 2189.68  4884.9 2183.59  4893.5 2181.08  4898.6 2182.51  4915.4 2177.15
  4935.7 2173.86  4951.7 2169.41  4956.8 2171.42  4966.2 2169.06  4974.8 2169.20
  4981.0 2168.88  4981.5 2168.38  4992.2 2168.88  5006.9 2169.88  5021.3 2168.98
  5029.2 2171.50  5032.7 2170.92  5035.7 2170.42  5043.3 2172.56  5070.8 2172.71
  5149.1 2178.98  5213.0 2182.06  5299.7 2181.68  5447.8 2181.95  5552.9 2185.08
  5590.0 2187.15  5597.9 2188.97  5633.1 2190.31  5689.1 2196.87  5817.6 2206.50
#Mann=8,-1,0
  4813.7    0.07       0  4974.8    0.16       0  4981.0    0.07       0
  4992.2    0.16       0  5032.7    0.07       0  5043.3    0.16       0
  5299.7    0.07       0  5552.9    0.16       0
Bank Sta=4981,4992.2
Exp/Cntr=0.3,0.1

Type RM Length L Ch R = 1,9428,499,499,499
BEGIN DESCRIPTION:
Bitter Creek Trib10 11.0
END DESCRIPTION:
XS GIS Cut Line= 3
      1410205.02      6829887.99      1410375.33      6829759.41
      1410955.00      6829138.00
#Sta/Elev= 30
  4786.6 2191.95  4872.9 2189.31  4900.0 2187.33  4914.6 2183.35  4922.1 2182.74
  4936.9 2179.85  4954.2 2172.63  4972.9 2169.33  4987.1 2170.06  4993.7 2169.00
  4997.0 2165.11  5001.3 2164.88  5001.8 2164.38  5014.3 2164.88  5015.1 2166.69
  5030.0 2170.71  5043.0 2171.52  5050.3 2169.57  5071.3 2169.54  5262.3 2174.21
  5283.8 2173.12  5290.7 2171.50  5319.0 2169.12  5347.3 2169.22  5368.8 2170.67
  5389.8 2174.80  5443.1 2176.66  5637.5 2181.20  5689.4 2183.57  5849.8 2193.10
#Mann=8,-1,0
  4786.6    0.07       0  4922.1    0.16       0  4954.2    0.07       0
  5001.3    0.07       0  5014.3    0.07       0  5030.0    0.16       0
  5443.1    0.07       0  5689.4    0.16       0
Bank Sta=5001.3,5014.3
Exp/Cntr=0.3,0.1

Type RM Length L Ch R = 1,8929,496,496,496
BEGIN DESCRIPTION:
Bitter Creek Trib10 10.0
END DESCRIPTION:
XS GIS Cut Line= 3
      1410205.01      6830237.99      1410815.00      6829648.06
      1411155.00      6829038.00
#Sta/Elev= 30
  4151.4 2205.41  4285.8 2195.74  4306.9 2195.84  4335.2 2192.47  4399.0 2188.22
  4483.9 2183.93  4575.7 2181.31  4695.9 2183.81  4702.1 2182.31  4710.0 2183.20
  4731.3 2174.95  4752.4 2170.83  4887.0 2167.04  4929.4 2168.31  4971.9 2165.94
  4979.5 2161.45  4980.0 2160.95  4992.6 2161.45  4993.0 2162.81  4996.5 2164.71
  5002.9 2164.71  5008.0 2166.97  5013.8 2165.98  5065.8 2170.81  5132.6 2176.53
  5273.5 2181.78  5500.7 2194.43  5528.1 2197.58  5641.2 2205.58  5698.4 2213.22
#Mann=6,-1,0
  4151.4    0.07       0  4702.1    0.16       0  4979.5    0.07       0
  4992.6    0.16       0  5065.8    0.07       0  5273.5    0.16       0
Bank Sta=4979.5,4992.6
Exp/Cntr=0.3,0.1

Type RM Length L Ch R = 1,8433,499,499,499
BEGIN DESCRIPTION:
Bitter Creek Trib10 9.0
END DESCRIPTION:
XS GIS Cut Line= 3
      1410405.00      6830288.00      1411004.32      6830072.16
      1411404.98      6829738.02
#Sta/Elev= 30
  4363.0 2195.10  4389.0 2192.92  4644.0 2177.04  4692.5 2172.77  4705.4 2170.28
  4730.8 2171.13  4736.1 2169.14  4756.2 2169.49  4848.3 2162.97  4862.5 2164.26
  4873.2 2162.68  4877.7 2157.20  4878.2 2156.70  4890.9 2157.20  4904.4 2161.64
  4915.7 2162.44  4965.8 2160.51  4971.1 2158.54  4985.3 2161.43  4996.5 2164.28
  5031.7 2164.37  5039.5 2165.87  5046.0 2164.86  5060.3 2168.88  5111.7 2171.34
  5245.1 2171.45  5322.9 2174.24  5422.2 2181.18  5450.8 2189.31  5521.7 2196.52
#Mann=7,-1,0
  4363.0    0.16       0  4389.0    0.07       0  4877.7    0.07       0
  4890.9    0.07       0  4985.3    0.16       0  5111.7    0.07       0
  5322.9    0.16       0
Bank Sta=4877.7,4890.9
Exp/Cntr=0.3,0.1

Type RM Length L Ch R = 1,7934,454,454,454
BEGIN DESCRIPTION:
Bitter Creek Trib10 8.0
END DESCRIPTION:
XS GIS Cut Line= 3
      1411005.04      6830487.97      1411168.24      6830351.56
      1411455.01      6829737.97
#Sta/Elev= 30
  4787.3 2189.79  4837.3 2187.82  4843.9 2182.83  4851.7 2181.79  4858.2 2177.48
  4865.5 2175.70  4879.0 2173.10  4929.7 2170.20  4936.3 2167.88  4950.6 2166.01
  4957.1 2162.98  4971.4 2159.43  5002.1 2159.86  5006.8 2157.12  5008.4 2154.67
  5008.9 2154.17  5021.6 2154.67  5024.1 2159.67  5052.5 2160.20  5081.2 2163.97
  5136.4 2167.99  5206.5 2169.67  5248.7 2169.62  5360.6 2170.48  5432.6 2173.27
  5548.8 2181.08  5577.9 2188.58  5589.0 2190.31  5650.5 2195.77  5677.3 2198.92
#Mann=7,-1,0
  4787.3    0.07       0  5008.4    0.07       0  5021.6    0.07       0
  5206.5    0.16       0  5248.7    0.07       0  5432.6    0.16       0
  5650.5    0.07       0
Bank Sta=5008.4,5021.6
Exp/Cntr=0.3,0.1

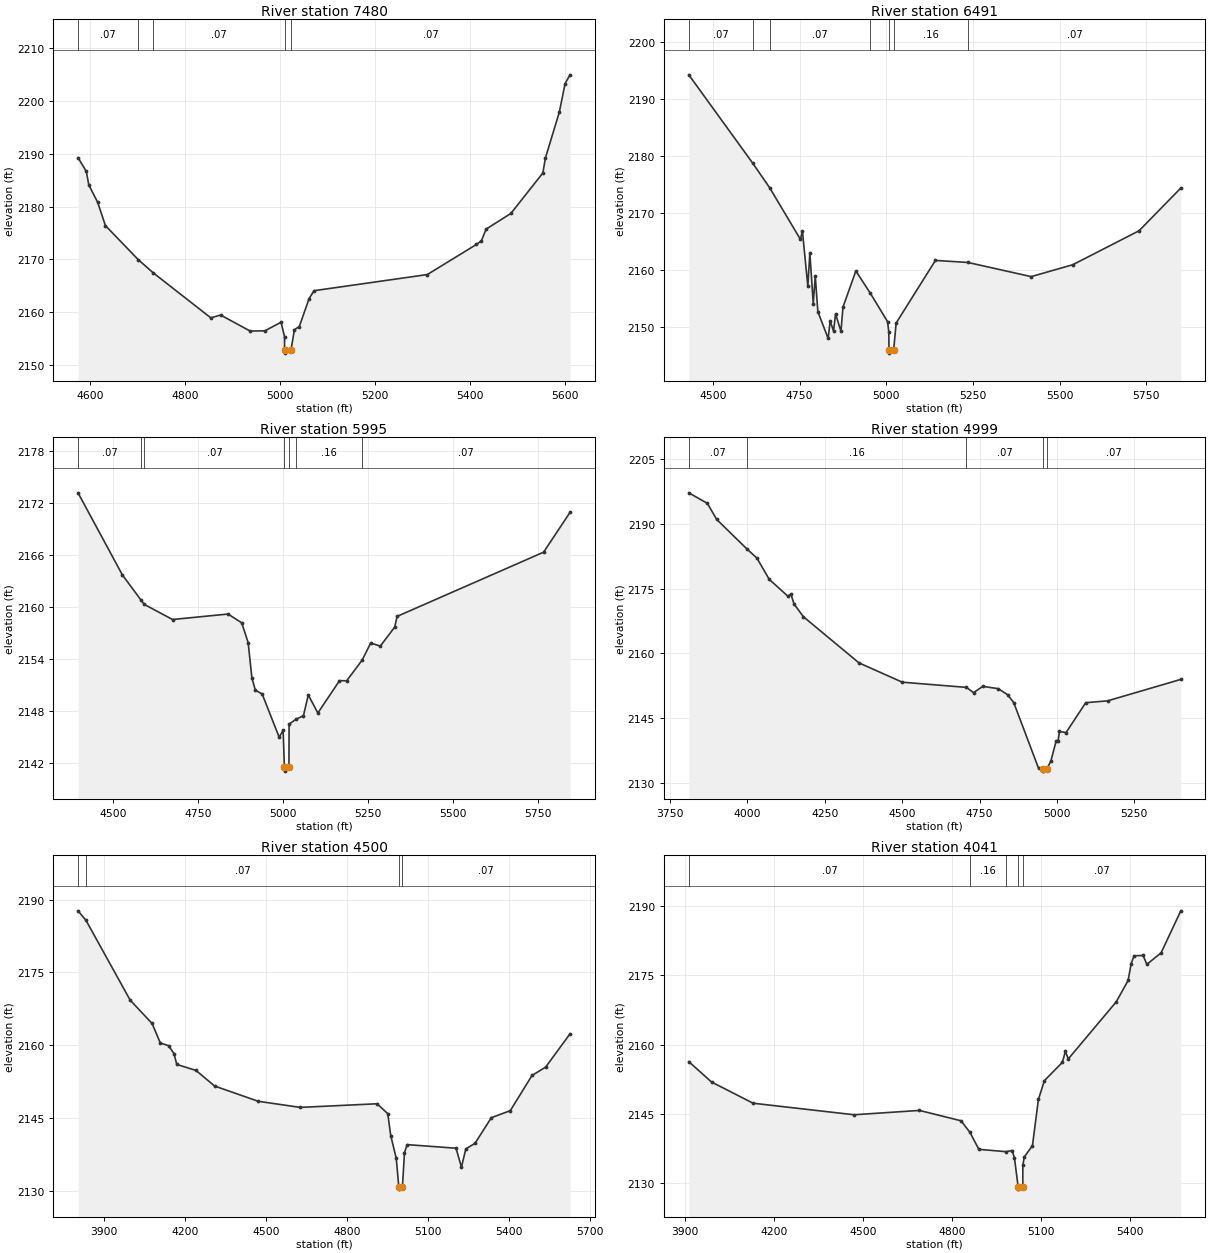
Type RM Length L Ch R = 1,7480,989,989,989
BEGIN DESCRIPTION:
Bitter Creek Trib10 7.0
END DESCRIPTION:
XS GIS Cut Line= 3
      1411054.98      6830537.99      1411465.79      6830647.67
      1412055.04      6830487.99
#Sta/Elev= 30
  4574.8 2189.27  4592.3 2186.66  4597.5 2184.10  4616.2 2180.81  4632.4 2176.42
  4701.5 2169.97  4732.7 2167.50  4854.3 2158.95  4875.0 2159.48  4937.1 2156.45
  4968.1 2156.49  5002.2 2158.12  5009.5 2155.39  5009.6 2152.77  5010.1 2152.27
  5023.0 2152.77  5030.3 2156.70  5040.6 2157.31  5061.3 2162.61  5071.7 2164.09
  5310.0 2167.14  5413.6 2172.85  5424.0 2173.54  5433.8 2175.74  5486.1 2178.72
  5553.3 2186.37  5558.7 2189.21  5588.0 2197.90  5600.1 2203.30  5610.5 2204.95
#Mann=5,-1,0
  4574.8    0.07       0  4701.5    0.16       0  4732.7    0.07       0
  5009.6    0.07       0  5023.0    0.07       0
Bank Sta=5009.6,5023
Exp/Cntr=0.3,0.1

Type RM Length L Ch R = 1,6491,496,496,496
BEGIN DESCRIPTION:
Bitter Creek Trib10 6.0
END DESCRIPTION:
XS GIS Cut Line= 3
      1410804.98      6830937.99      1411294.53      6831228.18
      1411905.00      6830638.00
#Sta/Elev= 30
  4430.9 2194.29  4614.8 2178.78  4664.4 2174.38  4752.6 2165.35  4758.4 2166.77
  4774.0 2157.11  4779.8 2162.96  4789.6 2154.06  4795.4 2158.88  4802.9 2152.62
  4832.5 2147.93  4838.3 2150.99  4848.1 2149.22  4853.9 2152.24  4869.5 2149.17
  4875.3 2153.43  4912.4 2159.78  4954.2 2155.86  5003.7 2150.88  5007.5 2149.02
  5007.9 2145.83  5008.4 2145.33  5021.3 2145.83  5028.6 2150.63  5141.8 2161.64
  5235.4 2161.28  5417.8 2158.79  5538.0 2160.89  5728.8 2166.86  5849.1 2174.37
#Mann=7,-1,0
  4430.9    0.07       0  4614.8    0.16       0  4664.4    0.07       0
  4954.2    0.16       0  5007.9    0.07       0  5021.3    0.16       0
  5235.4    0.07       0
Bank Sta=5007.9,5021.3
Exp/Cntr=0.3,0.1

Type RM Length L Ch R = 1,5995,996,996,996
BEGIN DESCRIPTION:
Bitter Creek Trib10 5.0
END DESCRIPTION:
XS GIS Cut Line= 3
      1410854.99      6831688.00      1411456.58      6831634.17
      1412055.00      6831038.00
#Sta/Elev= 30
  4396.0 2173.15  4526.5 2163.71  4582.3 2160.76  4591.1 2160.31  4674.3 2158.57
  4837.8 2159.20  4877.9 2158.19  4897.0 2155.91  4908.0 2151.84  4918.1 2150.44
  4938.2 2150.00  4988.4 2145.01  5000.0 2145.83  5003.6 2141.62  5004.1 2141.12
  5017.1 2141.62  5017.4 2146.53  5038.4 2147.10  5059.8 2147.50  5074.0 2149.89
  5102.2 2147.81  5165.9 2151.53  5187.1 2151.52  5232.3 2153.88  5257.8 2155.86
  5286.1 2155.51  5328.5 2157.70  5335.6 2158.93  5766.9 2166.32  5844.7 2170.90
#Mann=7,-1,0
  4396.0    0.07       0  4582.3    0.16       0  4591.1    0.07       0
  5003.6    0.07       0  5017.1    0.07       0  5038.4    0.16       0
  5232.3    0.07       0
Bank Sta=5003.6,5017.1
Exp/Cntr=0.3,0.1

Type RM Length L Ch R = 1,4999,499,499,499
BEGIN DESCRIPTION:
Bitter Creek Trib10 4.0
END DESCRIPTION:
XS GIS Cut Line= 3
      1410405.03      6832288.00      1411594.53      6832289.17
      1411879.75      6832008.30
#Sta/Elev= 30
  3810.5 2197.22  3870.5 2194.78  3900.5 2191.06  3998.2 2184.22  4030.5 2182.10
  4070.5 2177.16  4130.5 2173.28  4140.5 2173.72  4150.5 2171.47  4180.5 2168.52
  4360.5 2157.80  4500.5 2153.33  4707.6 2152.13  4730.5 2150.91  4760.5 2152.36
  4810.5 2151.83  4840.5 2150.44  4860.5 2148.59  4940.5 2133.41  4953.7 2133.22
  4954.2 2132.72  4967.3 2133.22  4980.5 2135.07  4997.7 2139.77  5003.8 2139.77
  5008.2 2141.92  5029.4 2141.65  5093.1 2148.58  5163.8 2149.01  5400.3 2153.98
#Mann=5,-1,0
  3810.5    0.07       0  3998.2    0.16       0  4707.6    0.07       0
  4953.7    0.07       0  4967.3    0.07       0
Bank Sta=4953.7,4967.3
Exp/Cntr=0.3,0.1

Type RM Length L Ch R = 1,4500,459,459,459
BEGIN DESCRIPTION:
Bitter Creek Trib10 3.0
END DESCRIPTION:
XS GIS Cut Line= 3
      1410555.03      6832887.99      1411731.64      6832664.73
      1412355.05      6832738.01
#Sta/Elev= 30
  3802.4 2187.72  3831.9 2185.76  3995.8 2169.30  4077.2 2164.48  4107.7 2160.46
  4138.3 2159.90  4158.6 2158.26  4168.8 2156.03  4240.0 2154.80  4309.1 2151.58
  4471.0 2148.43  4626.8 2147.17  4911.8 2147.92  4951.5 2145.88  4962.7 2141.32
  4983.1 2136.64  4992.4 2130.81  4992.9 2130.31  5006.0 2130.81  5013.5 2137.81
  5023.5 2139.49  5204.8 2138.75  5224.9 2134.85  5241.1 2138.61  5275.2 2139.76
  5335.7 2145.04  5406.1 2146.50  5486.7 2153.76  5537.0 2155.47  5627.7 2162.34
#Mann=4,-1,0
  3802.4    0.16       0  3831.9    0.07       0  4992.4    0.07       0
  5006.0    0.07       0
Bank Sta=4992.4,5006
Exp/Cntr=0.3,0.1

Type RM Length L Ch R = 1,4041,492,492,492
BEGIN DESCRIPTION:
Bitter Creek Trib10 4466
END DESCRIPTION:
XS GIS Cut Line= 3
      1410918.49      6832957.75      1412005.07      6832987.97
      1412571.06      6832918.82
#Sta/Elev= 30
  3913.0 2156.29  3989.5 2151.88  4129.6 2147.28  4469.7 2144.78  4689.8 2145.72
  4829.9 2143.48  4860.2 2140.94  4889.9 2137.29  4980.8 2136.79  5002.5 2137.03
  5010.0 2135.35  5022.3 2129.17  5022.8 2128.67  5038.0 2129.17  5038.1 2133.86
  5043.1 2135.65  5070.5 2138.10  5090.6 2148.11  5110.8 2152.18  5171.2 2156.13
  5181.3 2158.49  5191.3 2156.89  5352.5 2169.23  5392.8 2173.88  5402.9 2177.54
  5413.0 2179.22  5443.2 2179.29  5455.8 2177.37  5503.7 2179.85  5570.2 2188.96
#Mann=5,-1,0
  3913.0    0.07       0  4860.2    0.16       0  4980.8    0.07       0
  5022.3    0.07       0  5038.0    0.07       0
Bank Sta=5022.3,5038
Exp/Cntr=0.3,0.1

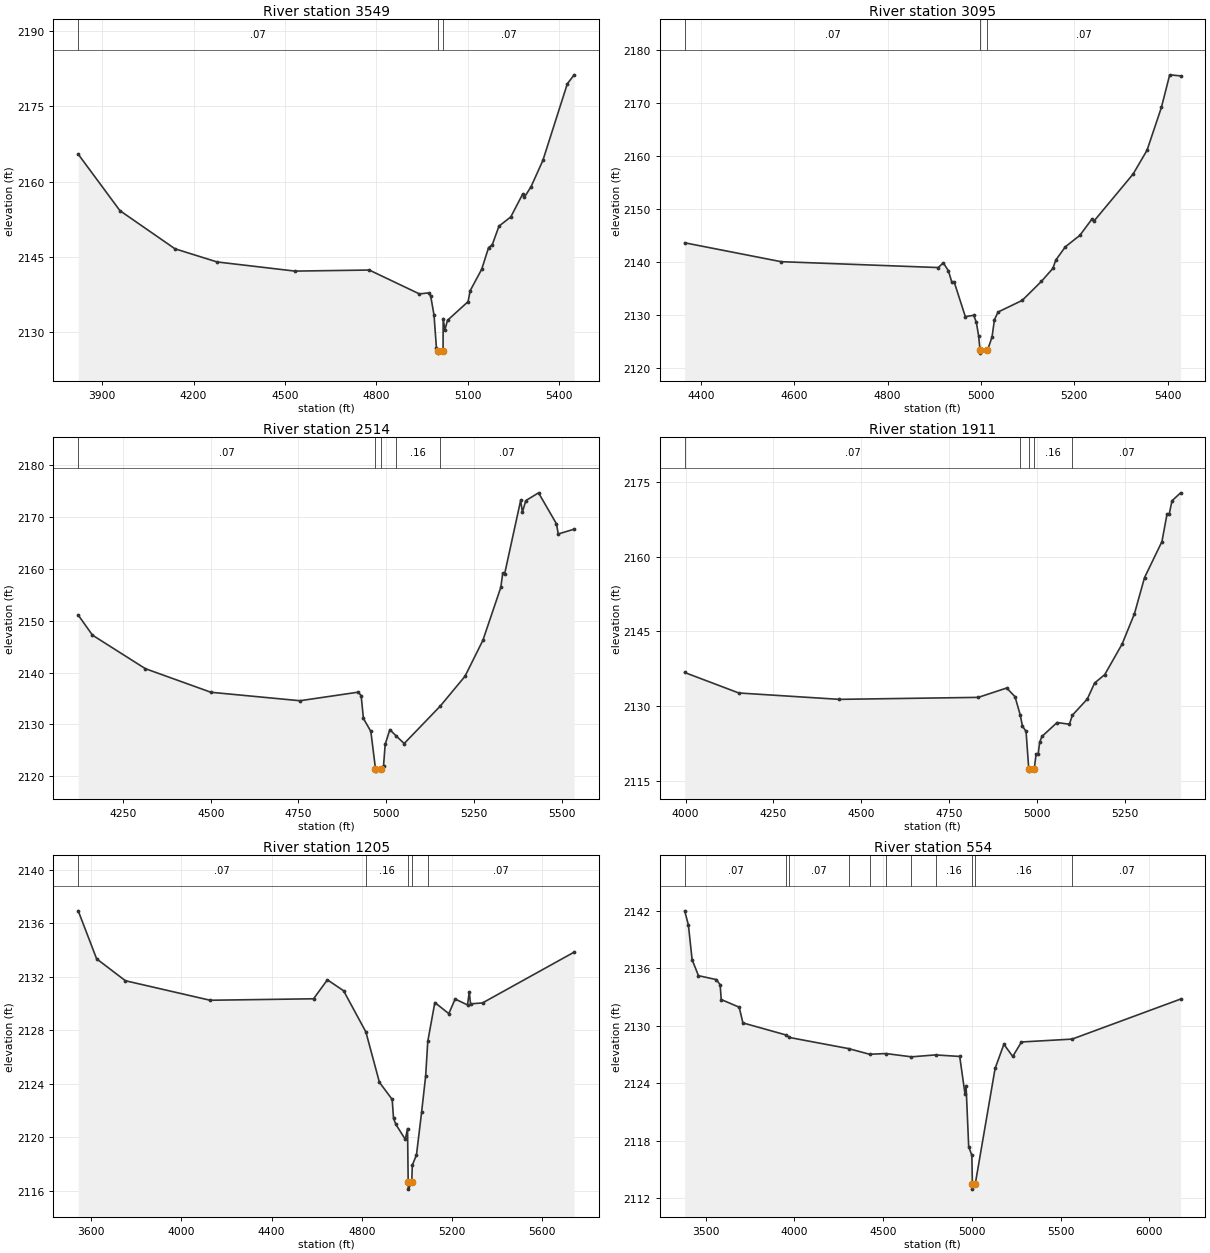
Type RM Length L Ch R = 1,3549,454,454,454
BEGIN DESCRIPTION:
Bitter Creek Trib10 2.0
END DESCRIPTION:
XS GIS Cut Line= 3
      1410796.09      6833033.27      1411904.88      6833432.88
      1412304.97      6833637.98
#Sta/Elev= 30
  3821.4 2165.49  3958.4 2154.25  4139.1 2146.66  4277.3 2144.04  4533.1 2142.22
  4776.9 2142.43  4941.5 2137.68  4972.2 2137.88  4978.9 2137.17  4989.5 2133.48
  4997.4 2126.98  5003.5 2126.39  5004.0 2125.89  5019.2 2126.39  5019.6 2132.77
  5025.2 2130.51  5033.9 2132.43  5101.3 2136.14  5108.4 2138.34  5146.2 2142.60
  5168.7 2146.91  5180.6 2147.44  5202.8 2151.17  5241.6 2153.01  5280.3 2157.52
  5286.0 2156.89  5308.2 2159.04  5346.9 2164.25  5427.2 2179.51  5449.6 2181.29
#Mann=3,-1,0
  3821.4    0.07       0  5003.5    0.07       0  5019.2    0.07       0
Bank Sta=5003.5,5019.2
Exp/Cntr=0.3,0.1

Type RM Length L Ch R = 1,3095,581,581,581
BEGIN DESCRIPTION:
Bitter Creek Trib10 1.0
END DESCRIPTION:
XS GIS Cut Line= 3
      1411105.01      6833488.01      1411689.23      6833736.84
      1412105.00      6833838.00
#Sta/Elev= 30
  4365.0 2143.68  4571.5 2140.12  4908.3 2139.01  4919.3 2139.89  4930.2 2138.41
  4937.4 2136.29  4942.8 2136.24  4966.5 2129.75  4984.5 2130.01  4990.1 2128.68
  4995.1 2126.07  4998.1 2123.37  4998.6 2122.87  5013.8 2123.37  5023.7 2125.89
  5028.9 2129.19  5036.8 2130.63  5088.3 2132.81  5129.4 2136.39  5154.1 2138.85
  5160.3 2140.41  5180.9 2142.93  5211.8 2145.07  5237.5 2148.11  5242.7 2147.83
  5326.1 2156.65  5355.9 2161.13  5386.7 2169.21  5404.5 2175.36  5427.9 2175.16
#Mann=3,-1,0
  4365.0    0.07       0  4998.1    0.07       0  5013.8    0.07       0
Bank Sta=4998.1,5013.8
Exp/Cntr=0.3,0.1

Type RM Length L Ch R = 1,2514,603,603,603
BEGIN DESCRIPTION:
Bitter Creek Trib10 4271
END DESCRIPTION:
XS GIS Cut Line= 3
      1410899.98      6833788.18      1411634.72      6834268.12
      1412160.05      6834163.25
#Sta/Elev= 30
  4122.4 2151.11  4163.0 2147.23  4313.8 2140.75  4500.8 2136.19  4754.2 2134.56
  4920.1 2136.21  4928.7 2135.55  4935.2 2131.13  4956.3 2128.64  4969.5 2121.46
  4970.0 2120.96  4985.2 2121.46  4992.5 2122.00  4997.2 2126.13  5010.5 2128.97
  5028.5 2127.76  5051.3 2126.29  5153.8 2133.50  5224.6 2139.28  5275.6 2146.23
  5326.6 2156.44  5332.2 2159.19  5337.3 2158.98  5383.2 2173.24  5388.3 2171.01
  5398.0 2173.22  5434.2 2174.72  5485.3 2168.73  5490.4 2166.77  5535.7 2167.70
#Mann=5,-1,0
  4122.4    0.07       0  4969.5    0.07       0  4985.2    0.07       0
  5028.5    0.16       0  5153.8    0.07       0
Bank Sta=4969.5,4985.2
Exp/Cntr=0.3,0.1

Type RM Length L Ch R = 1,1911,706,706,706
BEGIN DESCRIPTION:
Bitter Creek Trib10 4272
END DESCRIPTION:
XS GIS Cut Line= 4
      1411060.03      6834413.29      1411760.10      6834798.33
      1411954.69      6834738.33      1412270.06      6834478.38
#Sta/Elev= 30
  3997.4 2136.77  4151.4 2132.66  4437.5 2131.38  4832.9 2131.78  4913.8 2133.66
  4937.5 2131.91  4952.3 2128.25  4958.5 2126.03  4968.9 2124.94  4976.5 2117.48
  4977.0 2116.98  4992.2 2117.48  4997.5 2120.42  5003.4 2120.42  5007.6 2122.79
  5014.1 2123.94  5057.1 2126.73  5092.3 2126.39  5100.6 2128.20  5143.0 2131.43
  5164.0 2134.66  5192.7 2136.34  5242.2 2142.48  5277.3 2148.56  5306.0 2155.81
  5355.5 2163.03  5369.9 2168.51  5376.3 2168.57  5384.2 2171.23  5408.7 2172.82
#Mann=5,-1,0
  3997.4    0.07       0  4952.3    0.16       0  4976.5    0.07       0
  4992.2    0.16       0  5100.6    0.07       0
Bank Sta=4976.5,4992.2
Exp/Cntr=0.3,0.1

Type RM Length L Ch R = 1,1205,651,651,651
BEGIN DESCRIPTION:
Bitter Creek Trib10 4273
END DESCRIPTION:
XS GIS Cut Line= 4
      1410894.34      6834689.16      1412292.02      6835101.72
      1412450.59      6835142.56      1412699.15      6834621.34
#Sta/Elev= 30
  3542.7 2136.94  3624.3 2133.35  3751.9 2131.71  4127.3 2130.25  4586.0 2130.36
  4647.3 2131.78  4719.2 2130.96  4817.9 2127.88  4878.0 2124.11  4934.6 2122.83
  4940.5 2121.41  4951.0 2120.96  4992.7 2119.84  5002.6 2120.65  5005.5 2116.62
  5006.0 2116.12  5021.3 2116.62  5023.7 2117.91  5042.2 2118.68  5065.0 2121.88
  5082.9 2124.58  5092.3 2127.17  5123.6 2130.08  5185.5 2129.25  5213.7 2130.34
  5268.5 2129.90  5276.3 2130.88  5281.8 2129.98  5335.0 2130.05  5741.2 2133.85
#Mann=5,-1,0
  3542.7    0.07       0  4817.9    0.16       0  5005.5    0.07       0
  5021.3    0.16       0  5092.3    0.07       0
Bank Sta=5005.5,5021.3
Exp/Cntr=0.3,0.1

Type RM Length L Ch R = 1,554,0,0,0
BEGIN DESCRIPTION:
Bitter Creek Trib10 4274
END DESCRIPTION:
XS GIS Cut Line= 4
      1410776.29      6834758.60      1412104.94      6835683.03
      1412511.28      6835307.22      1412699.93      6834713.45
#Sta/Elev= 30
  3381.4 2142.01  3402.4 2140.53  3423.3 2136.91  3459.1 2135.24  3560.3 2134.83
  3581.3 2134.29  3587.4 2132.75  3688.6 2131.95  3709.6 2130.31  3954.9 2129.04
  3971.6 2128.79  4304.9 2127.63  4423.1 2127.04  4516.3 2127.11  4659.6 2126.77
  4795.1 2126.97  4931.5 2126.81  4961.2 2122.90  4967.3 2123.74  4982.1 2117.40
  5000.0 2116.48  5002.9 2113.46  5003.4 2112.96  5018.7 2113.46  5131.0 2125.56
  5180.4 2128.08  5230.3 2126.81  5279.6 2128.32  5564.9 2128.62  6176.5 2132.80
#Mann=11,-1,0
  3381.4    0.07       0  3954.9    0.16       0  3971.6    0.07       0
  4304.9    0.16       0  4423.1    0.07       0  4516.3    0.16       0
  4659.6    0.07       0  4795.1    0.16       0  5002.9    0.07       0
  5018.7    0.16       0  5564.9    0.07       0
Bank Sta=5002.9,5018.7
Exp/Cntr=0.3,0.1

Chan Stop Cuts=-1