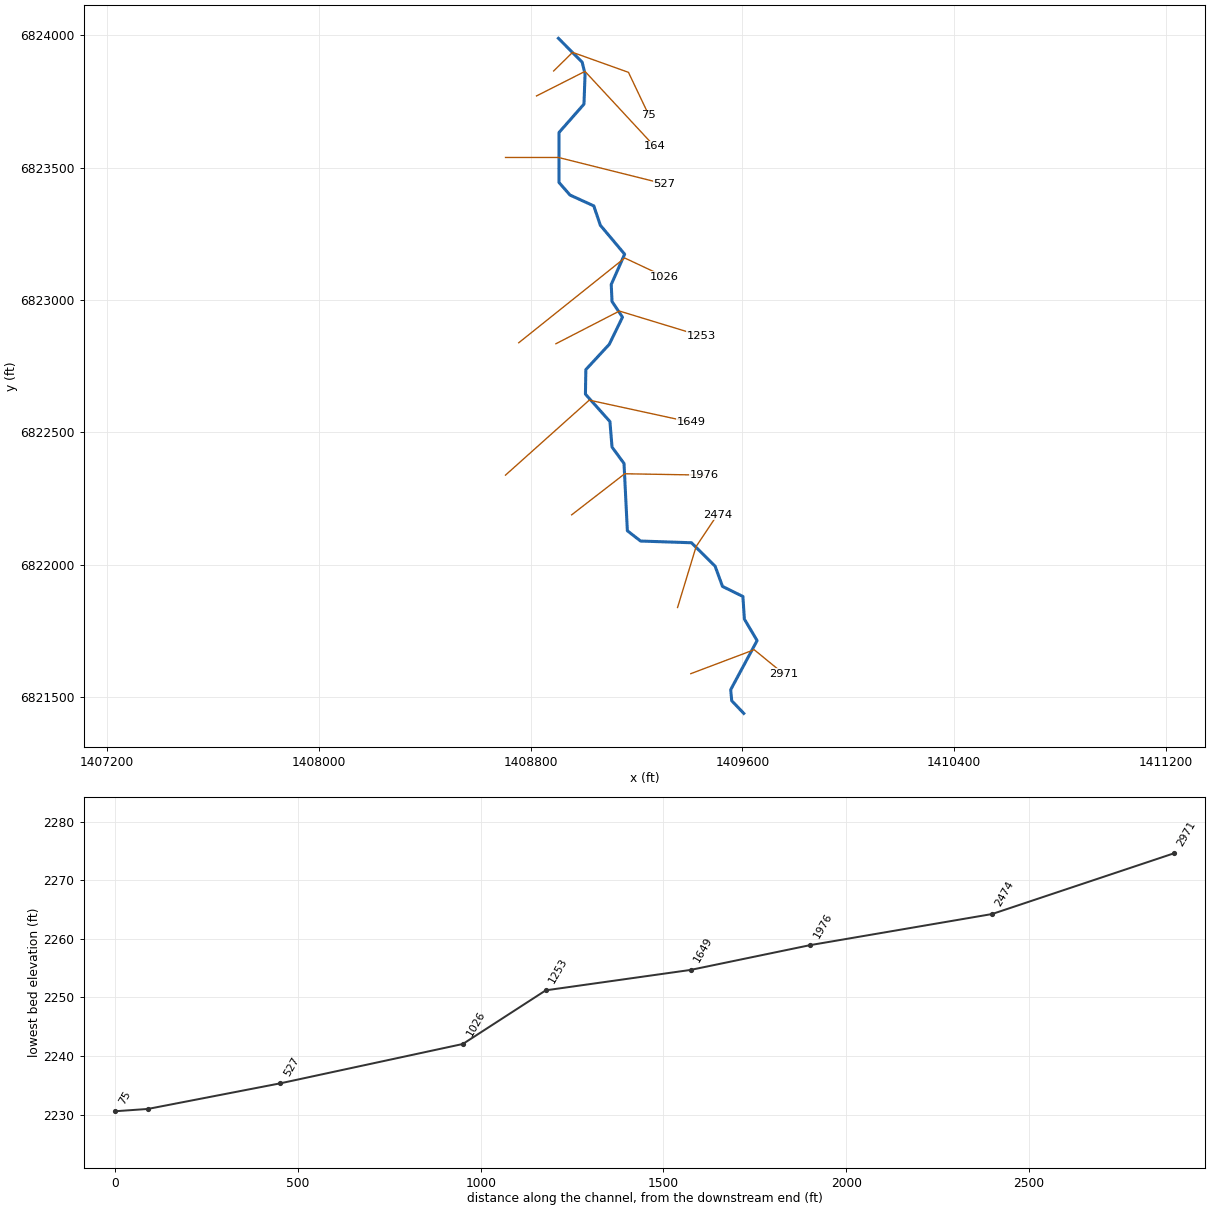
--- Bitter Creek Trib10T1.prj (project) ---

Proj Title=Bitter Creek Trib10T1 Base Level Engineering
Current Plan=p01
Default Exp/Contr=0.3,0.1
English Units
Geom File=g01
Flow File=f01
Plan File=p01
BEGIN DESCRIPTION:
Bitter Creek Trib10T1
END DESCRIPTION:

--- Bitter Creek Trib10T1.p01 (plan) ---

Plan Title=Multiple Run
Short Identifier=Multiple
Geom File=g01
Flow File=f01
Subcritical Flow
K Sum by GR= 0
Std Step Tol= 0.01
Critical Tol= 0.01
Num of Std Step Trials= 20
Max Error Tol= 0.3
Flow Tol Ratio= 0.001
Split Flow NTrial= 30
Split Flow Tol= 0.02
Split Flow Ratio= 0.02
Log Output Level= 0
Friction Slope Method= 1
Unsteady Friction Slope Method= 2
Unsteady Bridges Friction Slope Method= 1
Parabolic Critical Depth
Global Vel Dist=  1 , 1 , 1
Global Log Level= 0
CheckData=True
Encroach Param= -1, 0, 0, 0
BEGIN DESCRIPTION:
Multiple Run
END DESCRIPTION:

--- Bitter Creek Trib10T1.f01 (steady flow) ---

Flow Title=Multiple
Number of Profiles=7
Profile Names=10-year,25-year,50-year,1pct_min,100-year,1pct_plu,500-year
River Rch & RM= Bitter Creek Tri,Reach-1,2971
     372     542     689     437     872    1740    1412
River Rch & RM= Bitter Creek Tri,Reach-1,1976
     382     556     707     448     893    1782    1442
Boundary for River Rch & Prof#=Bitter Creek Tri,Reach-1,1
Up Type=0
Dn Type=3
Dn Slope=0.005
Boundary for River Rch & Prof#=Bitter Creek Tri,Reach-1,2
Up Type=0
Dn Type=3
Dn Slope=0.005
Boundary for River Rch & Prof#=Bitter Creek Tri,Reach-1,3
Up Type=0
Dn Type=3
Dn Slope=0.005
Boundary for River Rch & Prof#=Bitter Creek Tri,Reach-1,4
Up Type=0
Dn Type=3
Dn Slope=0.005
Boundary for River Rch & Prof#=Bitter Creek Tri,Reach-1,5
Up Type=0
Dn Type=3
Dn Slope=0.005
Boundary for River Rch & Prof#=Bitter Creek Tri,Reach-1,6
Up Type=0
Dn Type=3
Dn Slope=0.005
Boundary for River Rch & Prof#=Bitter Creek Tri,Reach-1,7
Up Type=0
Dn Type=3
Dn Slope=0.005

--- Bitter Creek Trib10T1.g01 (geometry) ---

Geom Title=Existing Conditions

River Reach=Bitter Creek Tri,Reach-1
Reach XY= 30
      1409605.00      6821438.00      1409559.60      6821485.64
      1409555.66      6821527.38      1409655.41      6821713.00
      1409607.42      6821794.05      1409601.81      6821879.65
      1409524.74      6821917.57      1409496.84      6821994.05
      1409407.47      6822082.55      1409215.26      6822088.98
      1409165.32      6822127.82      1409152.74      6822382.06
      1409107.36      6822443.98      1409099.46      6822540.42
      1409006.97      6822643.90      1409008.47      6822736.50
      1409096.86      6822831.96      1409146.96      6822934.68
      1409107.37      6822993.89      1409104.43      6823058.05
      1409155.04      6823172.66      1409063.19      6823281.98
      1409038.50      6823355.05      1408948.64      6823396.03
      1408906.98      6823443.67      1408907.06      6823632.14
      1409001.46      6823739.47      1409005.53      6823853.19
      1408994.61      6823897.84      1408905.00      6823988.00

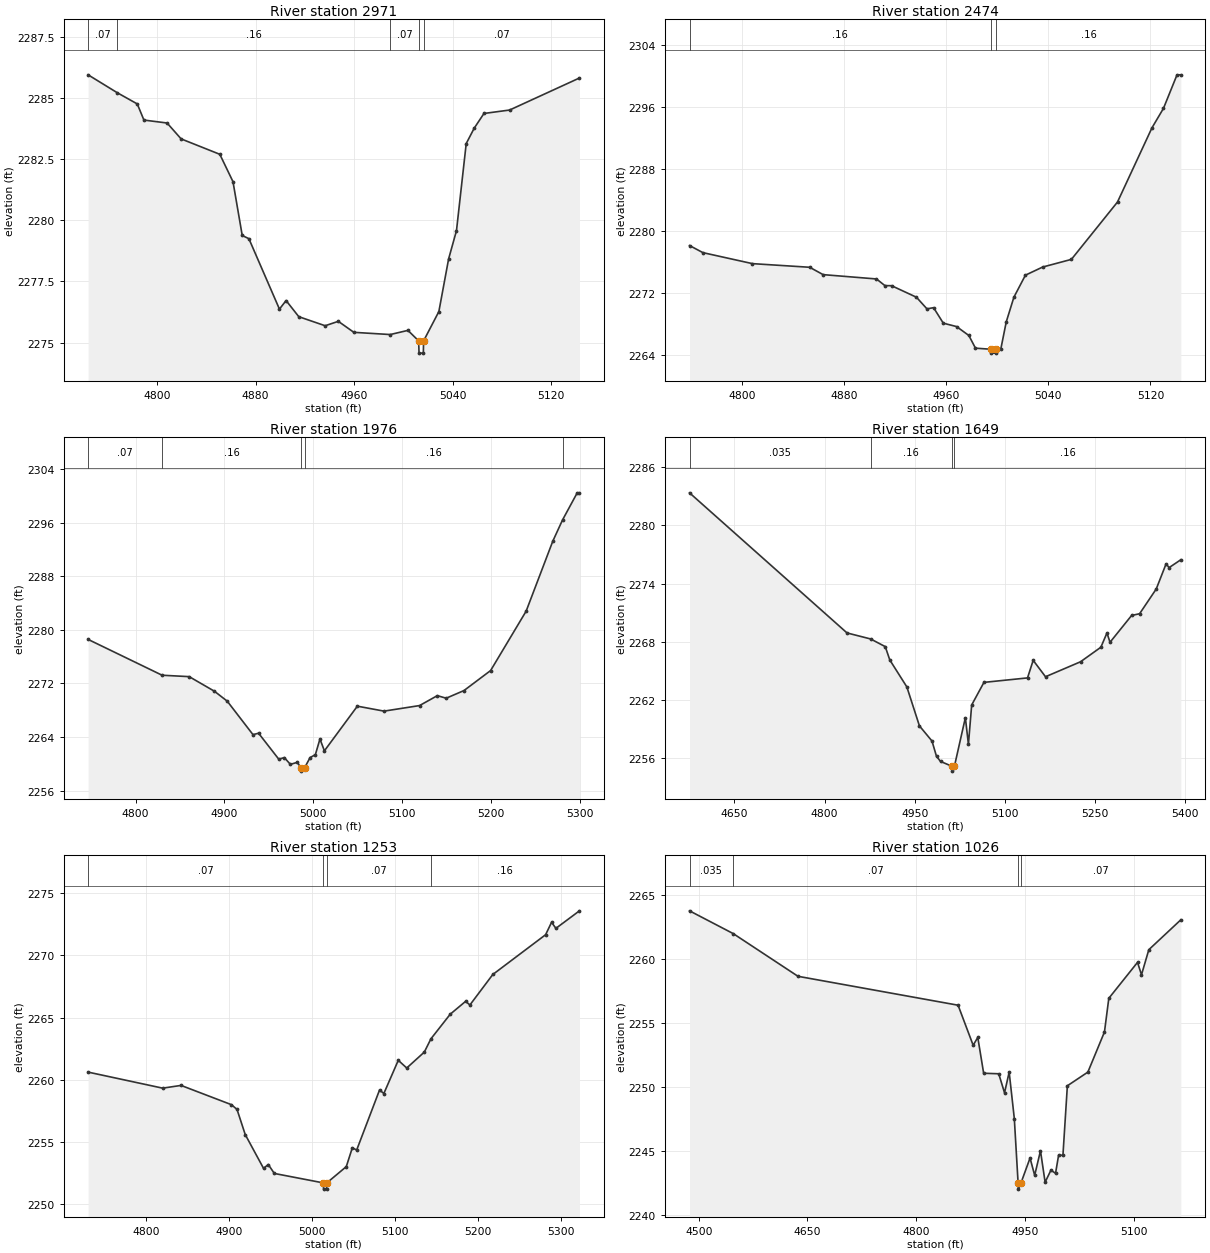
Type RM Length L Ch R = 1,2971,497,497,497
BEGIN DESCRIPTION:
Bitter Creek Trib10T1 5.0
END DESCRIPTION:
XS GIS Cut Line= 3
      1409405.00      6821588.00      1409644.49      6821678.45
      1409755.00      6821588.00
#Sta/Elev= 30
  4744.0 2285.95  4767.6 2285.22  4783.9 2284.76  4789.3 2284.10  4808.1 2283.98
  4819.5 2283.33  4850.9 2282.70  4861.6 2281.58  4869.1 2279.38  4874.5 2279.25
  4899.3 2276.37  4904.7 2276.72  4915.0 2276.06  4936.4 2275.69  4947.1 2275.87
  4959.7 2275.42  4989.2 2275.33  5003.6 2275.50  5012.3 2275.07  5012.6 2274.57
  5016.1 2274.57  5016.3 2275.07  5028.7 2276.27  5036.6 2278.42  5043.0 2279.58
  5050.9 2283.14  5057.4 2283.77  5065.3 2284.37  5086.1 2284.51  5142.8 2285.82
#Mann=5,-1,0
  4744.0    0.07       0  4767.6    0.16       0  4989.2    0.07       0
  5012.3    0.07       0  5016.3    0.07       0
Bank Sta=5012.3,5016.3
Exp/Cntr=0.3,0.1

Type RM Length L Ch R = 1,2474,498,498,498
BEGIN DESCRIPTION:
Bitter Creek Trib10T1 4.0
END DESCRIPTION:
XS GIS Cut Line= 3
      1409354.99      6821837.97      1409425.20      6822068.41
      1409505.02      6822188.03
#Sta/Elev= 30
  4759.1 2278.12  4769.6 2277.20  4808.4 2275.78  4853.2 2275.31  4863.7 2274.36
  4905.5 2273.80  4912.1 2272.94  4917.3 2272.93  4936.8 2271.44  4945.0 2269.94
  4950.2 2270.09  4957.8 2268.09  4968.2 2267.65  4977.8 2266.50  4983.0 2264.86
  4995.2 2264.72  4995.4 2264.22  4998.9 2264.22  4999.2 2264.72  5002.8 2264.72
  5007.1 2268.26  5013.1 2271.45  5022.1 2274.29  5035.6 2275.34  5058.1 2276.33
  5094.2 2283.74  5121.2 2293.33  5130.2 2295.84  5140.8 2300.17  5143.8 2300.17
#Mann=3,-1,0
  4759.1    0.16       0  4995.2    0.07       0  4999.2    0.16       0
Bank Sta=4995.2,4999.2
Exp/Cntr=0.3,0.1

Type RM Length L Ch R = 1,1976,327,327,327
BEGIN DESCRIPTION:
Bitter Creek Trib10T1 3.0
END DESCRIPTION:
XS GIS Cut Line= 3
      1408954.99      6822187.99      1409155.44      6822343.18
      1409454.99      6822338.00
#Sta/Elev= 30
  4746.5 2278.58  4829.8 2273.23  4860.3 2273.02  4888.7 2270.84  4903.1 2269.36
  4932.1 2264.36  4938.4 2264.57  4961.1 2260.70  4967.4 2260.93  4974.2 2259.92
  4981.9 2260.22  4986.2 2259.41  4986.5 2258.91  4990.2 2259.41  4996.4 2260.94
  5002.3 2261.36  5007.5 2263.71  5012.5 2261.94  5049.6 2268.61  5079.6 2267.87
  5119.6 2268.70  5139.6 2270.18  5149.6 2269.80  5169.6 2270.94  5199.6 2273.93
  5239.6 2282.80  5269.6 2293.25  5280.6 2296.43  5297.1 2300.47  5299.6 2300.47
#Mann=5,-1,0
  4746.5    0.07       0  4829.8    0.16       0  4986.2    0.07       0
  4990.2    0.16       0  5280.6    0.07       0
Bank Sta=4986.2,4990.2
Exp/Cntr=0.3,0.1

Type RM Length L Ch R = 1,1649,396,396,396
BEGIN DESCRIPTION:
Bitter Creek Trib10T1 2.0
END DESCRIPTION:
XS GIS Cut Line= 3
      1408705.00      6822338.00      1409021.44      6822621.26
      1409405.00      6822538.00
#Sta/Elev= 30
  4575.3 2283.34  4837.3 2268.91  4876.6 2268.29  4900.9 2267.50  4908.4 2266.13
  4936.8 2263.35  4957.7 2259.34  4978.6 2257.78  4986.1 2256.20  4992.8 2255.68
  5011.8 2255.18  5012.1 2254.68  5015.9 2255.18  5034.1 2260.18  5039.2 2257.44
  5044.6 2261.49  5065.0 2263.82  5137.5 2264.28  5146.9 2266.09  5167.4 2264.40
  5225.6 2265.94  5259.5 2267.44  5269.6 2268.91  5274.7 2267.95  5310.6 2270.71
  5323.9 2270.89  5351.6 2273.44  5367.9 2276.02  5373.0 2275.64  5392.5 2276.45
#Mann=4,-1,0
  4575.3   0.035       0  4876.6    0.16       0  5011.8    0.07       0
  5015.9    0.16       0
Bank Sta=5011.8,5015.9
Exp/Cntr=0.3,0.1

Type RM Length L Ch R = 1,1253,227,227,227
BEGIN DESCRIPTION:
Bitter Creek Trib10T1 4182
END DESCRIPTION:
XS GIS Cut Line= 3
      1408895.38      6822834.25      1409135.21      6822957.83
      1409444.01      6822863.78
#Sta/Elev= 30
  4730.2 2260.61  4820.1 2259.32  4842.3 2259.54  4903.1 2257.99  4909.8 2257.61
  4919.7 2255.59  4941.8 2252.87  4947.5 2253.18  4954.8 2252.46  5014.0 2251.70
  5014.2 2251.20  5017.8 2251.20  5018.1 2251.70  5041.6 2253.01  5048.9 2254.53
  5054.1 2254.34  5081.7 2259.17  5086.9 2258.89  5104.3 2261.56  5114.5 2260.94
  5135.7 2262.22  5143.7 2263.29  5167.0 2265.27  5185.5 2266.30  5190.7 2266.01
  5218.3 2268.46  5282.0 2271.66  5289.2 2272.66  5294.4 2272.17  5322.8 2273.58
#Mann=4,-1,0
  4730.2    0.07       0  5014.0    0.07       0  5018.1    0.07       0
  5143.7    0.16       0
Bank Sta=5014,5018.1
Exp/Cntr=0.3,0.1

Type RM Length L Ch R = 1,1026,499,499,499
BEGIN DESCRIPTION:
Bitter Creek Trib10T1 1.0
END DESCRIPTION:
XS GIS Cut Line= 3
      1408754.97      6822837.97      1409155.36      6823158.21
      1409305.00      6823088.00
#Sta/Elev= 30
  4487.3 2263.80  4547.6 2262.02  4637.0 2258.68  4857.9 2256.42  4878.7 2253.29
  4885.1 2253.90  4893.2 2251.10  4914.0 2251.06  4922.0 2249.57  4928.4 2251.19
  4935.5 2247.56  4940.7 2242.54  4941.0 2242.04  4944.8 2242.54  4957.2 2244.47
  4963.6 2243.12  4971.6 2245.04  4978.0 2242.58  4986.0 2243.52  4992.4 2243.28
  4996.6 2244.69  5002.6 2244.69  5008.7 2250.12  5037.0 2251.19  5059.9 2254.33
  5065.9 2256.96  5105.5 2259.77  5111.0 2258.80  5121.1 2260.76  5165.3 2263.10
#Mann=4,-1,0
  4487.3   0.035       0  4547.6    0.07       0  4940.7    0.07       0
  4944.8    0.07       0
Bank Sta=4940.7,4944.8
Exp/Cntr=0.3,0.1

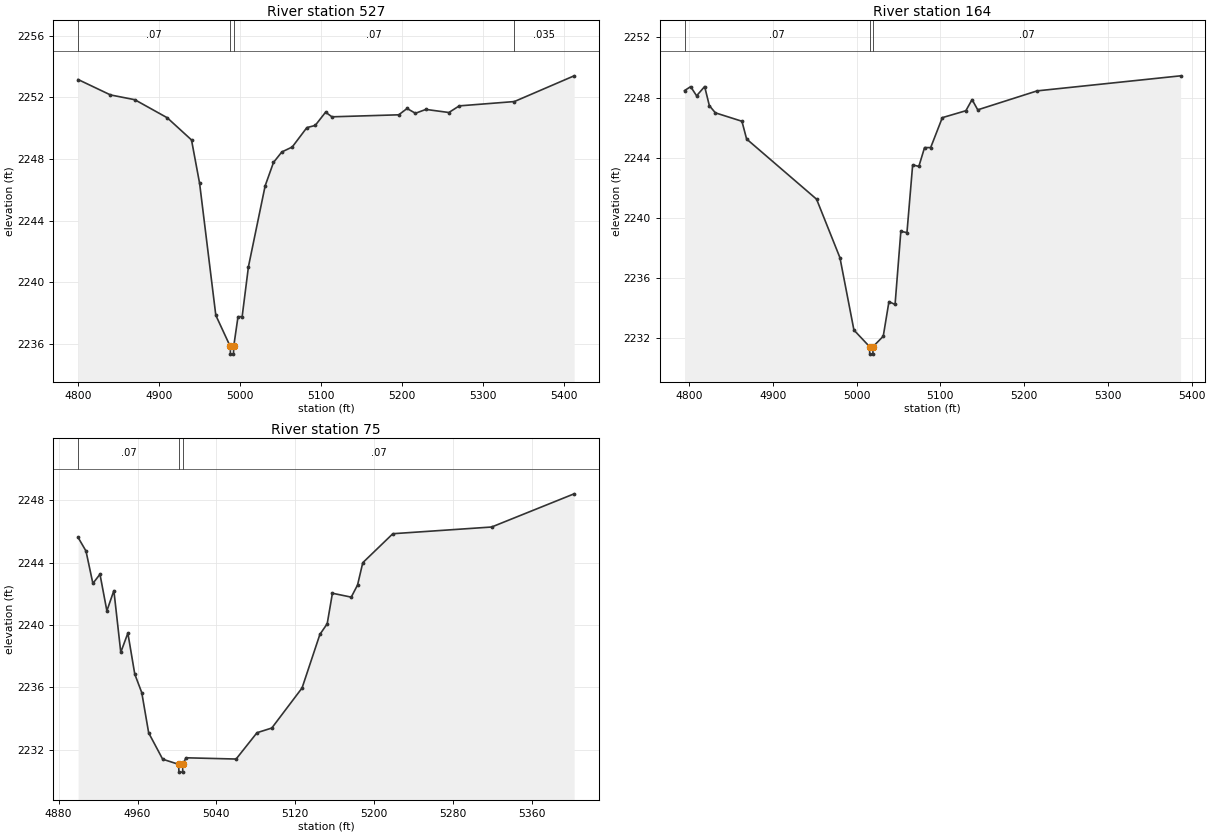
Type RM Length L Ch R = 1,527,363,363,363
BEGIN DESCRIPTION:
Bitter Creek Trib10T1 0.1
END DESCRIPTION:
XS GIS Cut Line= 3
      1408705.04      6823538.00      1408904.84      6823538.00
      1409305.03      6823437.99
#Sta/Elev= 30
  4800.2 2253.15  4840.2 2252.15  4870.2 2251.84  4910.2 2250.67  4940.2 2249.23
  4950.2 2246.41  4970.2 2237.85  4988.0 2235.83  4988.3 2235.33  4992.0 2235.33
  4992.3 2235.83  4997.6 2237.76  5002.7 2237.76  5010.5 2241.01  5031.1 2246.25
  5041.4 2247.77  5051.7 2248.45  5064.5 2248.77  5082.6 2250.03  5092.9 2250.17
  5105.7 2251.03  5113.5 2250.73  5196.0 2250.86  5206.3 2251.27  5216.6 2250.96
  5229.5 2251.21  5257.9 2251.01  5270.7 2251.44  5338.7 2251.72  5412.5 2253.39
#Mann=4,-1,0
  4800.2    0.07       0  4988.0    0.07       0  4992.3    0.07       0
  5338.7   0.035       0
Bank Sta=4988,4992.3
Exp/Cntr=0.3,0.1

Type RM Length L Ch R = 1,164,89,89,89
BEGIN DESCRIPTION:
Bitter Creek Trib10T1 4275
END DESCRIPTION:
XS GIS Cut Line= 3
      1408822.15      6823770.40      1409005.33      6823863.11
      1409268.29      6823579.45
#Sta/Elev= 30
  4794.7 2248.47  4802.0 2248.73  4809.1 2248.12  4818.7 2248.74  4824.3 2247.47
  4831.5 2246.99  4863.2 2246.43  4868.8 2245.25  4952.3 2241.25  4980.2 2237.36
  4996.9 2232.55  5015.5 2231.45  5015.8 2230.95  5019.5 2230.95  5019.8 2231.45
  5031.9 2232.14  5038.7 2234.44  5046.0 2234.25  5052.9 2239.11  5060.2 2239.03
  5067.0 2243.53  5074.4 2243.43  5081.2 2244.68  5088.5 2244.68  5102.4 2246.67
  5130.5 2247.13  5137.9 2247.87  5144.7 2247.19  5215.6 2248.45  5386.8 2249.45
#Mann=3,-1,0
  4794.7    0.07       0  5015.5    0.07       0  5019.8    0.07       0
Bank Sta=5015.5,5019.8
Exp/Cntr=0.3,0.1

Type RM Length L Ch R = 1,75,0,0,0
BEGIN DESCRIPTION:
Bitter Creek Trib10T1 4463
END DESCRIPTION:
XS GIS Cut Line= 4
      1408886.93      6823864.77      1408958.50      6823935.04
      1409169.49      6823859.57      1409246.32      6823698.10
#Sta/Elev= 30
  4899.7 2245.62  4907.7 2244.75  4914.7 2242.67  4921.9 2243.26  4928.9 2240.91
  4936.0 2242.21  4943.0 2238.25  4950.2 2239.48  4957.2 2236.85  4964.3 2235.66
  4971.3 2233.08  4985.5 2231.39  5001.7 2231.06  5002.0 2230.56  5005.7 2230.56
  5006.0 2231.06  5009.1 2231.48  5060.0 2231.40  5081.2 2233.09  5096.2 2233.39
  5126.9 2235.96  5145.0 2239.40  5152.4 2240.08  5157.7 2242.04  5176.8 2241.79
  5183.2 2242.57  5188.5 2244.00  5219.0 2245.86  5319.2 2246.29  5402.9 2248.42
#Mann=3,-1,0
  4899.7    0.07       0  5001.7    0.07       0  5006.0    0.07       0
Bank Sta=5001.7,5006
Exp/Cntr=0.3,0.1

Chan Stop Cuts=-1