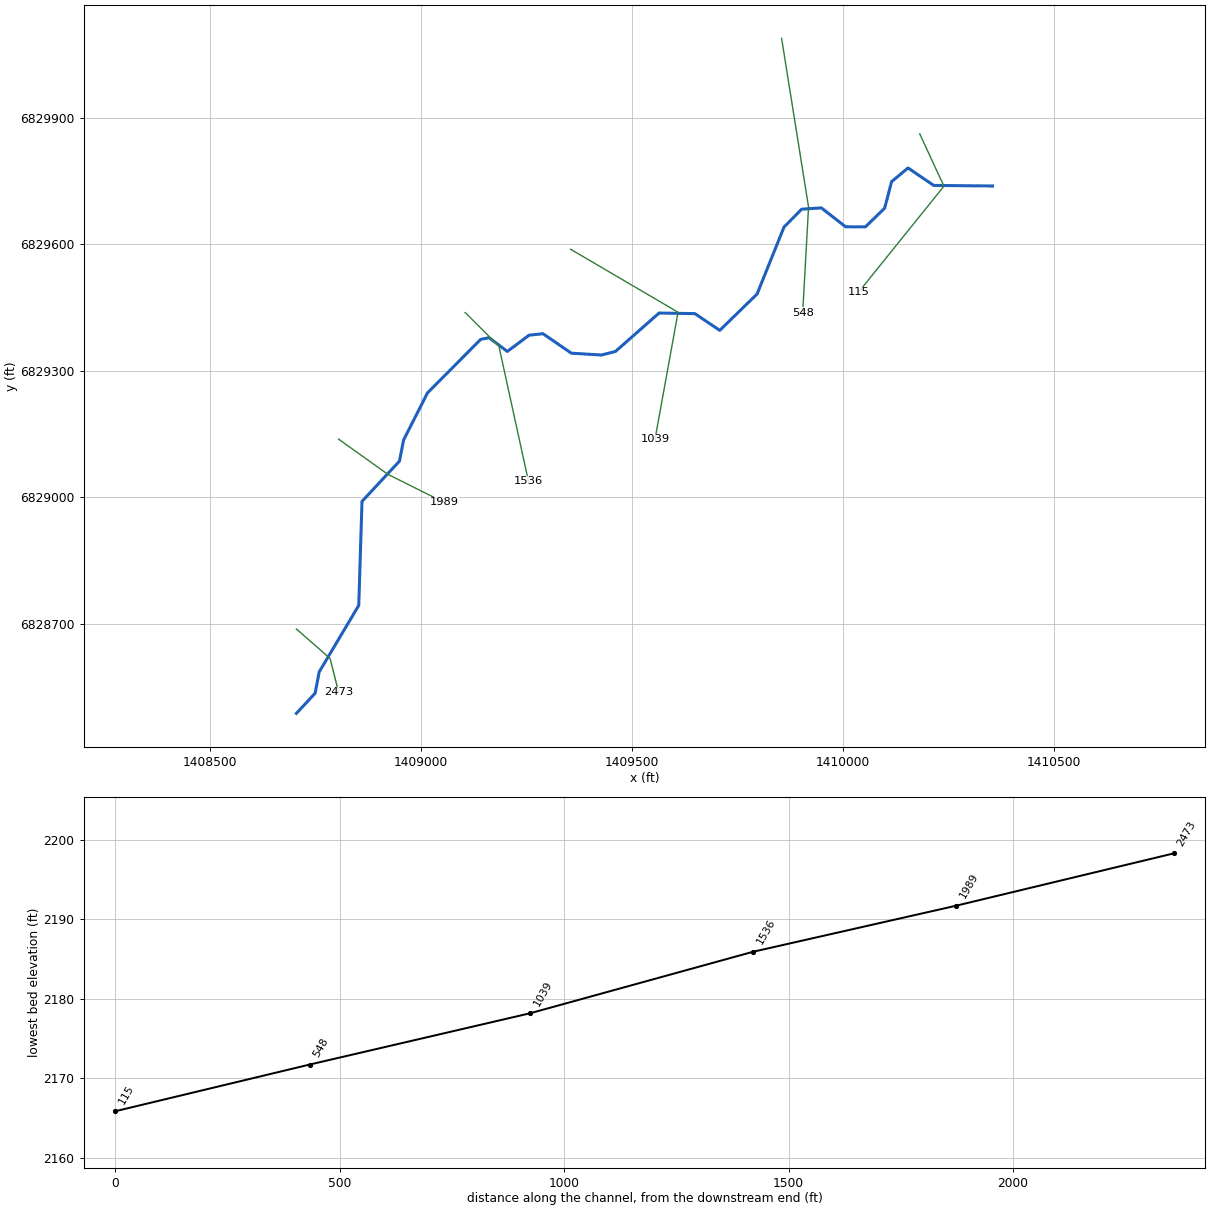
--- Bitter Creek Trib10T2.prj (project) ---

Proj Title=Bitter Creek Trib10T2 Base Level Engineering
Current Plan=p01
Default Exp/Contr=0.3,0.1
English Units
Geom File=g01
Flow File=f01
Plan File=p01
Y Axis Title=Elevation
X Axis Title(PF)=Main Channel Distance
X Axis Title(XS)=Station
BEGIN DESCRIPTION:
Bitter Creek Trib10T2
END DESCRIPTION:
DSS Export Rating Curves= 0
DSS Export Rating Curve Sorted= 0
DSS Export Volume Flow Curves= 0
DXF OffsetX= 0
DXF OffsetY= 0
DXF ScaleX= 1
DXF ScaleY= 10

--- Bitter Creek Trib10T2.p01 (plan) ---

Plan Title=Multiple Run
Short Identifier=Multiple
Geom File=g01
Flow File=f01
Subcritical Flow
K Sum by GR= 0
Std Step Tol= 0.01
Critical Tol= 0.01
Num of Std Step Trials= 20
Max Error Tol= 0.3
Flow Tol Ratio= 0.001
Split Flow NTrial= 30
Split Flow Tol= 0.02
Split Flow Ratio= 0.02
Log Output Level= 0
Friction Slope Method= 1
Unsteady Friction Slope Method= 2
Unsteady Bridges Friction Slope Method= 1
Parabolic Critical Depth
Global Vel Dist=  1 , 1 , 1
Global Log Level= 0
CheckData=True
Encroach Param= -1, 0, 0, 0
BEGIN DESCRIPTION:
Multiple Run
END DESCRIPTION:

--- Bitter Creek Trib10T2.f01 (steady flow) ---

Flow Title=Multiple
Number of Profiles=7
Profile Names=10-year,25-year,50-year,1pct_min,100-year,1pct_plu,500-year
River Rch & RM= Bitter Creek Tri,Reach-1,2473
     366     532     676     427     852    1701    1374
Boundary for River Rch & Prof#=Bitter Creek Tri,Reach-1,1
Up Type=0
Dn Type=3
Dn Slope=0.005
Boundary for River Rch & Prof#=Bitter Creek Tri,Reach-1,2
Up Type=0
Dn Type=3
Dn Slope=0.005
Boundary for River Rch & Prof#=Bitter Creek Tri,Reach-1,3
Up Type=0
Dn Type=3
Dn Slope=0.005
Boundary for River Rch & Prof#=Bitter Creek Tri,Reach-1,4
Up Type=0
Dn Type=3
Dn Slope=0.005
Boundary for River Rch & Prof#=Bitter Creek Tri,Reach-1,5
Up Type=0
Dn Type=3
Dn Slope=0.005
Boundary for River Rch & Prof#=Bitter Creek Tri,Reach-1,6
Up Type=0
Dn Type=3
Dn Slope=0.005
Boundary for River Rch & Prof#=Bitter Creek Tri,Reach-1,7
Up Type=0
Dn Type=3
Dn Slope=0.005

--- Bitter Creek Trib10T2.g01 (geometry) ---

Geom Title=Existing Conditions

River Reach=Bitter Creek Tri,Reach-1
Reach XY= 30
      1408705.00      6828488.00      1408749.33      6828535.64
      1408759.04      6828586.33      1408852.76      6828743.93
      1408860.47      6828990.45      1408949.15      6829085.71
      1408959.19      6829136.27      1409015.76      6829247.68
      1409141.66      6829374.36      1409161.66      6829378.40
      1409204.91      6829345.84      1409256.63      6829384.41
      1409289.58      6829387.85      1409356.59      6829341.73
      1409427.79      6829337.42      1409461.16      6829345.78
      1409564.64      6829436.90      1409649.52      6829435.51
      1409708.43      6829395.79      1409796.86      6829481.91
      1409860.73      6829640.62      1409902.45      6829683.01
      1409949.25      6829686.09      1410006.76      6829641.36
      1410053.58      6829641.04      1410099.25      6829685.44
      1410115.78      6829748.39      1410154.69      6829780.78
      1410215.40      6829739.35      1410355.00      6829738.00

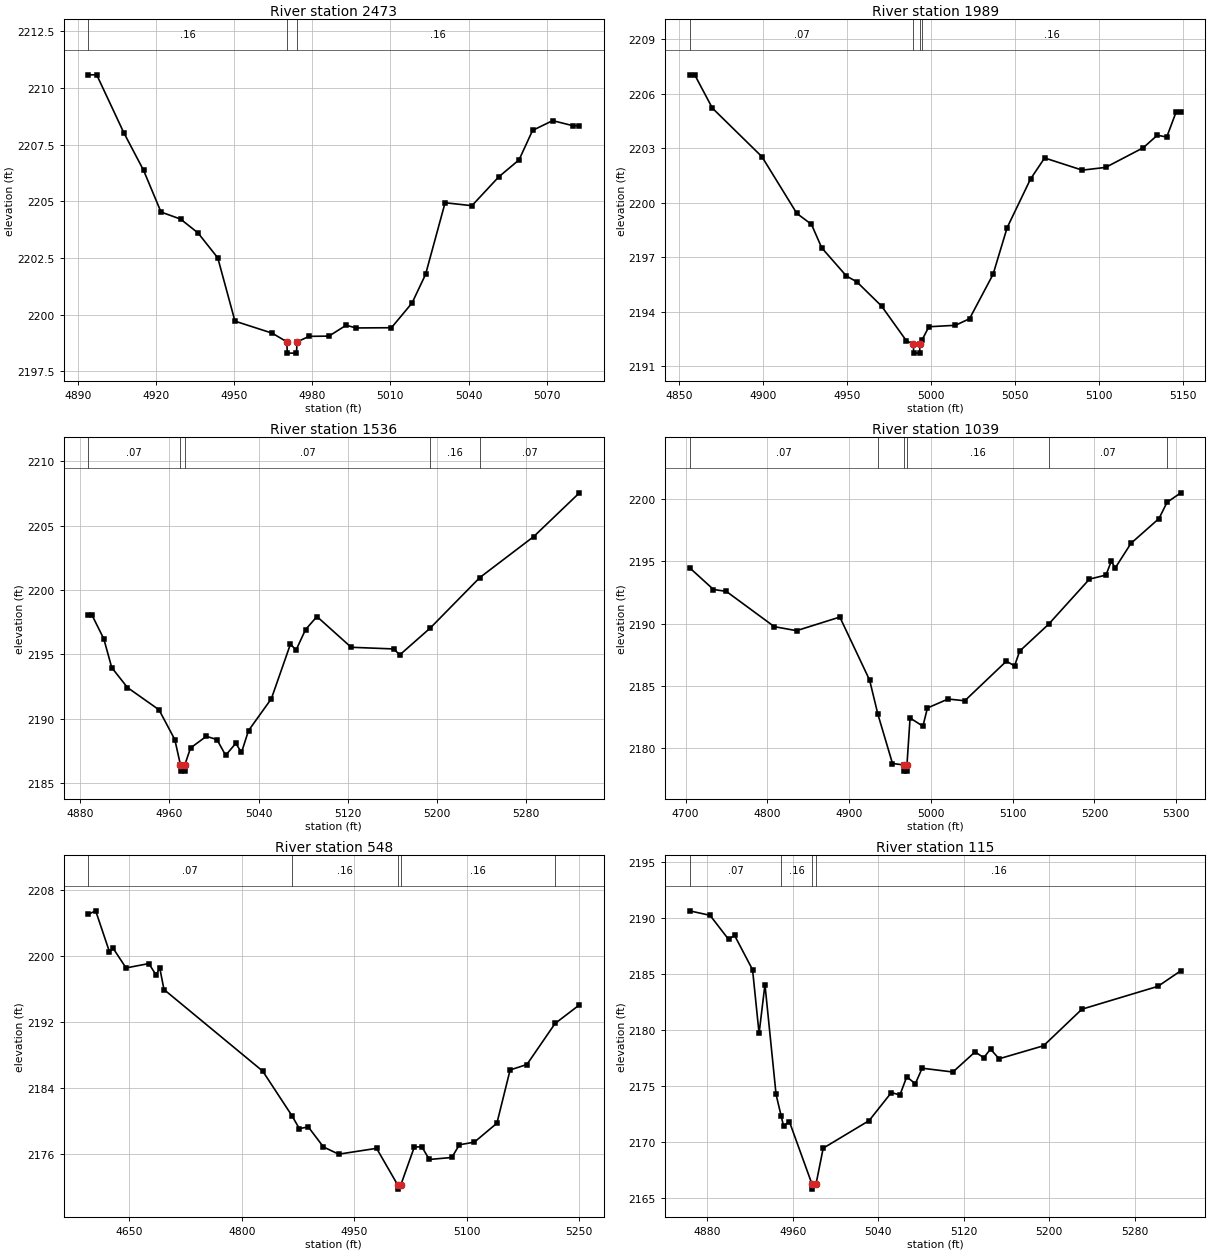
Type RM Length L Ch R = 1,2473,484,484,484
BEGIN DESCRIPTION:
Bitter Creek Trib10T2 4.0
END DESCRIPTION:
XS GIS Cut Line= 3
      1408705.03      6828687.97      1408784.84      6828618.07
      1408805.01      6828537.97
#Sta/Elev= 29
  4893.9 2210.58  4897.2 2210.58  4907.6 2208.03  4915.2 2206.37  4921.9 2204.53
  4929.4 2204.22  4936.1 2203.61  4943.7 2202.51  4950.3 2199.72  4964.6 2199.19
  4970.2 2198.81  4970.4 2198.31  4973.9 2198.31  4974.2 2198.81  4978.8 2199.05
  4986.4 2199.06  4993.0 2199.54  4996.8 2199.42  5010.4 2199.43  5018.3 2200.52
  5023.5 2201.78  5031.0 2204.94  5041.3 2204.81  5051.6 2206.08  5059.4 2206.83
  5064.6 2208.13  5072.3 2208.56  5080.0 2208.34  5082.6 2208.34
#Mann=3,-1,0
  4893.9    0.16       0  4970.2    0.07       0  4974.2    0.16       0
Bank Sta=4970.2,4974.2
Exp/Cntr=0.3,0.1

Type RM Length L Ch R = 1,1989,453,453,453
BEGIN DESCRIPTION:
Bitter Creek Trib10T2 3.0
END DESCRIPTION:
XS GIS Cut Line= 3
      1408804.97      6829138.02      1408921.94      6829054.55
      1409055.03      6828987.99
#Sta/Elev= 30
  4856.3 2207.03  4859.4 2207.03  4869.9 2205.20  4899.4 2202.53  4920.2 2199.41
  4928.9 2198.81  4935.0 2197.52  4949.7 2195.97  4955.9 2195.65  4970.6 2194.32
  4985.4 2192.41  4989.5 2192.23  4989.8 2191.73  4993.3 2191.73  4993.5 2192.23
  4994.7 2192.45  4998.8 2193.18  5014.6 2193.26  5023.0 2193.62  5037.0 2196.06
  5045.4 2198.63  5059.3 2201.30  5067.7 2202.46  5090.1 2201.79  5104.0 2201.94
  5126.4 2203.02  5134.8 2203.71  5140.4 2203.61  5146.0 2204.99  5148.8 2204.99
#Mann=4,-1,0
  4856.3    0.07       0  4989.5    0.07       0  4993.5    0.07       0
  4994.7    0.16       0
Bank Sta=4989.5,4993.5
Exp/Cntr=0.3,0.1

Type RM Length L Ch R = 1,1536,497,497,497
BEGIN DESCRIPTION:
Bitter Creek Trib10T2 2.0
END DESCRIPTION:
XS GIS Cut Line= 3
      1409105.01      6829437.99      1409184.97      6829358.28
      1409255.01      6829037.95
#Sta/Elev= 30
  4887.1 2198.05  4890.6 2198.05  4901.2 2196.20  4908.3 2193.97  4922.4 2192.42
  4950.7 2190.69  4964.9 2188.37  4969.9 2186.42  4970.2 2185.92  4973.7 2185.92
  4973.9 2186.42  4979.0 2187.72  4993.2 2188.63  5002.7 2188.37  5010.5 2187.15
  5019.6 2188.08  5024.7 2187.37  5031.0 2189.07  5051.5 2191.55  5068.6 2195.79
  5073.7 2195.34  5082.2 2196.93  5092.4 2197.94  5123.1 2195.55  5161.5 2195.42
  5166.6 2194.95  5194.1 2197.05  5238.5 2200.97  5286.9 2204.16  5327.9 2207.56
#Mann=5,-1,0
  4887.1    0.07       0  4969.9    0.07       0  4973.9    0.07       0
  5194.1    0.16       0  5238.5    0.07       0
Bank Sta=4969.9,4973.9
Exp/Cntr=0.3,0.1

Type RM Length L Ch R = 1,1039,491,491,491
BEGIN DESCRIPTION:
Bitter Creek Trib10T2 1.0
END DESCRIPTION:
XS GIS Cut Line= 3
      1409354.98      6829588.01      1409609.58      6829438.79
      1409555.00      6829138.01
#Sta/Elev= 30
  4704.9 2194.48  4734.2 2192.73  4749.9 2192.58  4808.6 2189.75  4835.8 2189.43
  4888.7 2190.52  4925.1 2185.47  4935.2 2182.74  4953.1 2178.78  4966.8 2178.67
  4967.1 2178.17  4970.6 2178.17  4970.8 2178.67  4974.6 2182.43  4990.3 2181.77
  4995.8 2183.23  5021.1 2183.95  5041.5 2183.81  5092.3 2186.98  5102.4 2186.61
  5108.6 2187.79  5143.9 2189.94  5193.9 2193.56  5214.2 2193.89  5220.5 2194.98
  5225.6 2194.47  5244.7 2196.43  5279.0 2198.42  5288.8 2199.72  5305.7 2200.48
#Mann=6,-1,0
  4704.9    0.07       0  4935.2    0.16       0  4966.8    0.07       0
  4970.8    0.16       0  5143.9    0.07       0  5288.8    0.16       0
Bank Sta=4966.8,4970.8
Exp/Cntr=0.3,0.1

Type RM Length L Ch R = 1,548,433,433,433
BEGIN DESCRIPTION:
Bitter Creek Trib10T2 0.1
END DESCRIPTION:
XS GIS Cut Line= 3
      1409855.00      6830087.98      1409918.91      6829687.95
      1409905.00      6829438.04
#Sta/Elev= 30
  4594.9 2205.05  4605.0 2205.48  4623.4 2200.50  4628.4 2200.92  4645.5 2198.55
  4675.9 2199.08  4685.5 2197.70  4690.5 2198.54  4696.1 2195.93  4827.8 2186.03
  4866.7 2180.63  4876.7 2179.05  4888.6 2179.26  4908.8 2176.83  4929.1 2175.95
  4979.7 2176.66  5007.9 2172.21  5008.2 2171.71  5012.0 2172.21  5030.0 2176.81
  5040.0 2176.86  5050.0 2175.31  5080.1 2175.55  5090.1 2177.09  5110.1 2177.41
  5140.2 2179.71  5157.8 2186.17  5180.2 2186.83  5217.8 2191.81  5250.3 2194.07
#Mann=5,-1,0
  4594.9    0.07       0  4866.7    0.16       0  5007.9    0.07       0
  5012.0    0.16       0  5217.8    0.07       0
Bank Sta=5007.9,5012
Exp/Cntr=0.3,0.1

Type RM Length L Ch R = 1,115,0,0,0
BEGIN DESCRIPTION:
Bitter Creek Trib10T2 4277
END DESCRIPTION:
XS GIS Cut Line= 3
      1410182.46      6829861.56      1410239.76      6829737.56
      1410037.01      6829485.86
#Sta/Elev= 30
  4863.4 2190.64  4882.6 2190.24  4900.0 2188.09  4905.5 2188.46  4922.4 2185.39
  4928.5 2179.71  4934.0 2184.07  4944.4 2174.27  4949.2 2172.34  4951.4 2171.46
  4956.9 2171.84  4977.8 2166.33  4978.1 2165.83  4981.9 2166.33  4988.5 2169.48
  5031.5 2171.94  5052.3 2174.44  5060.3 2174.22  5066.7 2175.85  5074.7 2175.22
  5081.1 2176.61  5109.9 2176.27  5130.7 2178.07  5138.7 2177.54  5145.1 2178.31
  5153.1 2177.45  5194.7 2178.61  5230.6 2181.87  5301.8 2183.91  5323.2 2185.30
#Mann=4,-1,0
  4863.4    0.07       0  4949.2    0.16       0  4977.8    0.07       0
  4981.9    0.16       0
Bank Sta=4977.8,4981.9
Exp/Cntr=0.3,0.1

Chan Stop Cuts=-1