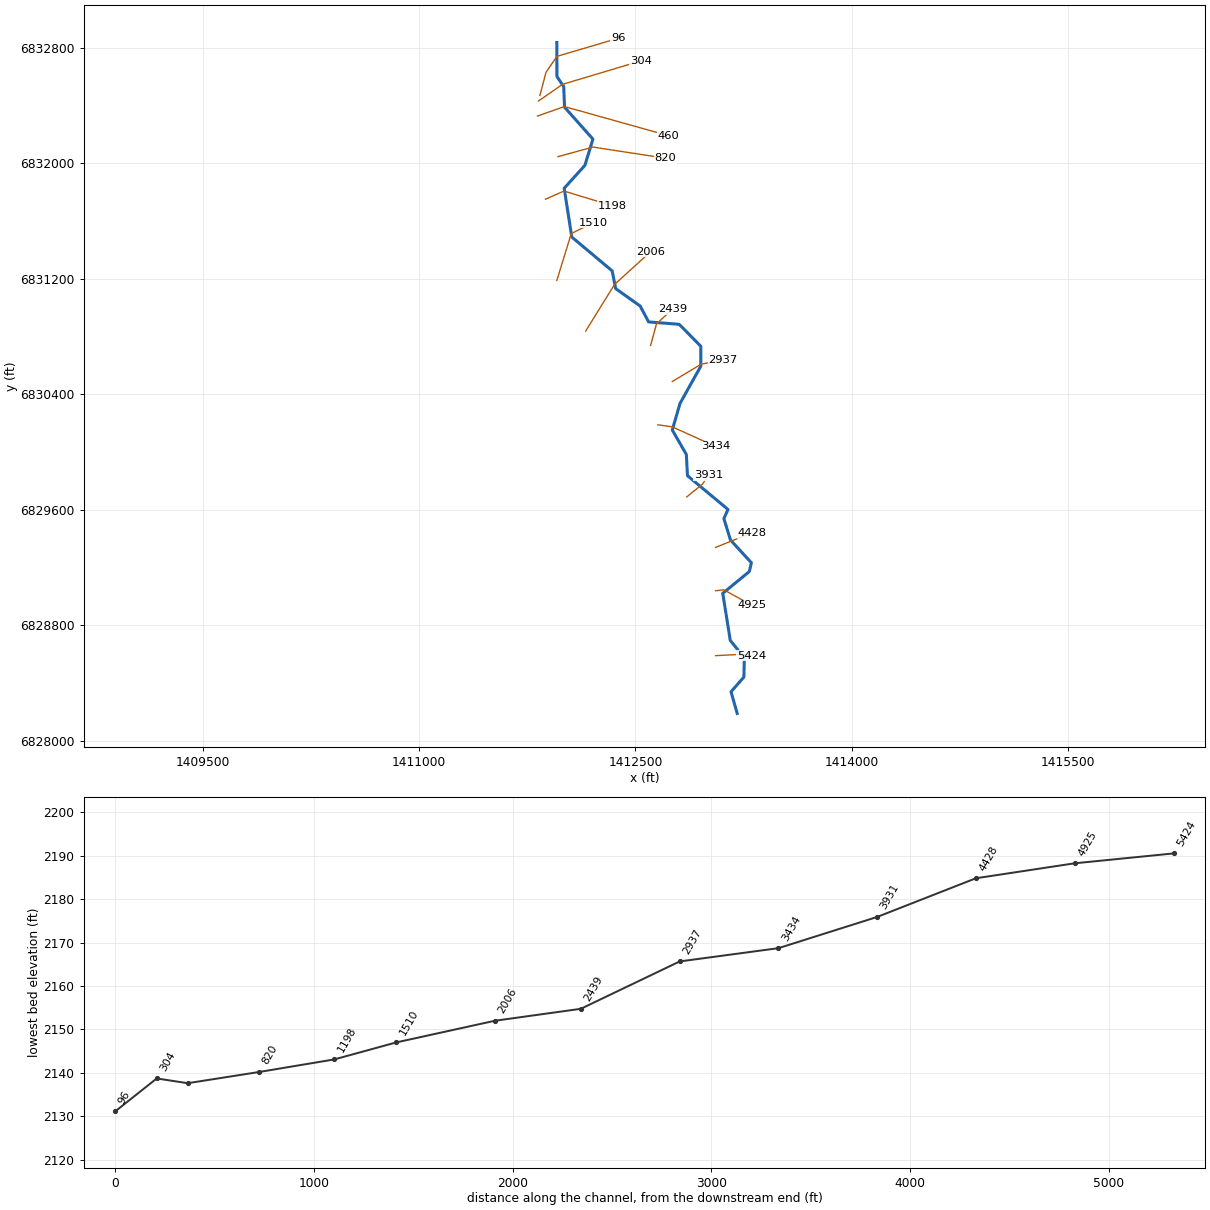
--- Bitter Creek Trib10T3.prj (project) ---

Proj Title=Bitter Creek Trib10T3 Base Level Engineering
Current Plan=p01
Default Exp/Contr=0.3,0.1
English Units
Geom File=g01
Flow File=f01
Plan File=p01
BEGIN DESCRIPTION:
Bitter Creek Trib10T3
END DESCRIPTION:

--- Bitter Creek Trib10T3.p01 (plan) ---

Plan Title=Multiple Run
Short Identifier=Multiple
Geom File=g01
Flow File=f01
Subcritical Flow
K Sum by GR= 0
Std Step Tol= 0.01
Critical Tol= 0.01
Num of Std Step Trials= 20
Max Error Tol= 0.3
Flow Tol Ratio= 0.001
Split Flow NTrial= 30
Split Flow Tol= 0.02
Split Flow Ratio= 0.02
Log Output Level= 0
Friction Slope Method= 1
Unsteady Friction Slope Method= 2
Unsteady Bridges Friction Slope Method= 1
Parabolic Critical Depth
Global Vel Dist=  1 , 1 , 1
Global Log Level= 0
CheckData=True
Encroach Param= -1, 0, 0, 0
BEGIN DESCRIPTION:
Multiple Run
END DESCRIPTION:

--- Bitter Creek Trib10T3.f01 (steady flow) ---

Flow Title=Multiple
Number of Profiles=7
Profile Names=10-year,25-year,50-year,1pct_min,100-year,1pct_plu,500-year
River Rch & RM= Bitter Creek Tri,Reach-1,5424
     312     447     561     351     700    1398    1105
River Rch & RM= Bitter Creek Tri,Reach-1,2937
     337     485     611     383     764    1523    1209
Boundary for River Rch & Prof#=Bitter Creek Tri,Reach-1,1
Up Type=0
Dn Type=3
Dn Slope=0.005
Boundary for River Rch & Prof#=Bitter Creek Tri,Reach-1,2
Up Type=0
Dn Type=3
Dn Slope=0.005
Boundary for River Rch & Prof#=Bitter Creek Tri,Reach-1,3
Up Type=0
Dn Type=3
Dn Slope=0.005
Boundary for River Rch & Prof#=Bitter Creek Tri,Reach-1,4
Up Type=0
Dn Type=3
Dn Slope=0.005
Boundary for River Rch & Prof#=Bitter Creek Tri,Reach-1,5
Up Type=0
Dn Type=3
Dn Slope=0.005
Boundary for River Rch & Prof#=Bitter Creek Tri,Reach-1,6
Up Type=0
Dn Type=3
Dn Slope=0.005
Boundary for River Rch & Prof#=Bitter Creek Tri,Reach-1,7
Up Type=0
Dn Type=3
Dn Slope=0.005

--- Bitter Creek Trib10T3.g01 (geometry) ---

Geom Title=Existing Conditions

River Reach=Bitter Creek Tri,Reach-1
Reach XY= 30
      1413205.00      6828188.00      1413162.28      6828338.09
      1413251.45      6828439.47      1413254.63      6828572.83
      1413157.19      6828693.45      1413105.07      6829019.78
      1413288.95      6829170.95      1413303.44      6829231.91
      1413158.61      6829389.50      1413112.80      6829538.10
      1413141.36      6829601.34      1412860.36      6829835.30
      1412852.64      6829982.48      1412755.23      6830152.10
      1412808.83      6830336.42      1412952.77      6830593.93
      1412952.95      6830732.14      1412803.54      6830884.46
      1412591.33      6830901.23      1412532.14      6831011.83
      1412362.86      6831131.81      1412338.56      6831254.79
      1412058.54      6831489.47      1412006.04      6831827.56
      1412149.17      6831985.70      1412205.21      6832167.95
      1412008.54      6832389.47      1412002.61      6832532.47
      1411955.68      6832601.92      1411955.00      6832838.00

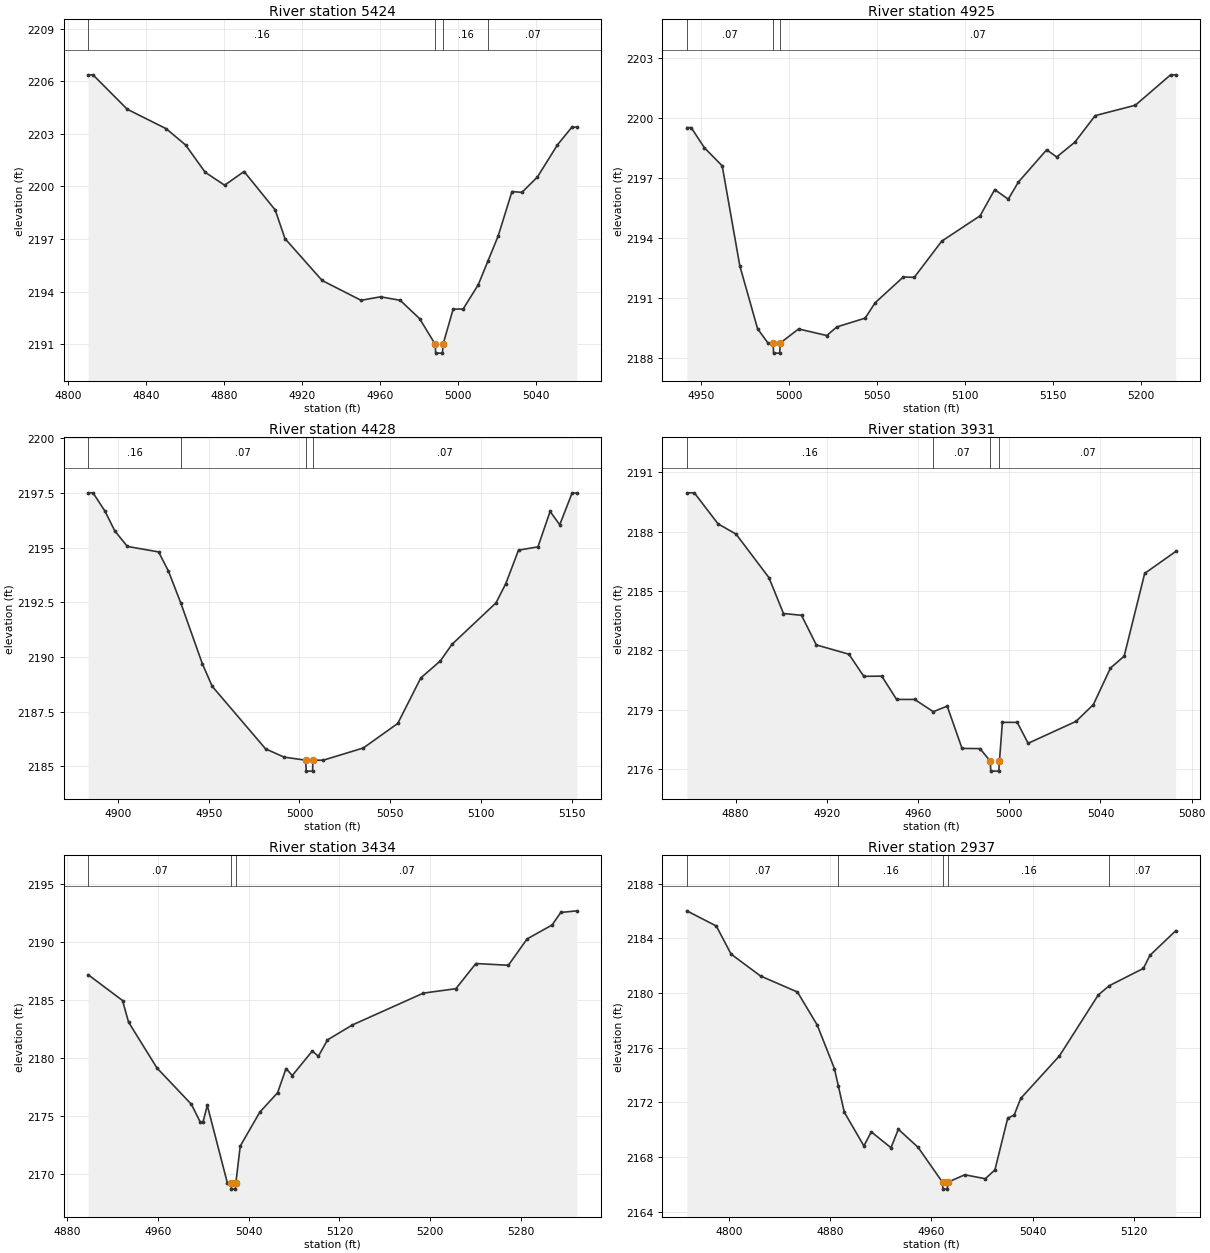
Type RM Length L Ch R = 1,5424,499,499,499
BEGIN DESCRIPTION:
Bitter Creek Trib10T3 8.0
END DESCRIPTION:
XS GIS Cut Line= 3
      1413054.96      6828588.00      1413244.50      6828597.79
      1413305.02      6828588.00
#Sta/Elev= 30
  4810.2 2206.36  4812.7 2206.36  4830.3 2204.40  4850.3 2203.29  4860.3 2202.36
  4870.3 2200.81  4880.3 2200.07  4890.3 2200.85  4906.3 2198.66  4911.3 2197.03
  4930.4 2194.64  4950.4 2193.51  4960.4 2193.71  4970.5 2193.51  4980.5 2192.46
  4988.5 2191.00  4988.7 2190.50  4992.2 2190.50  4992.5 2191.00  4997.7 2193.01
  5002.8 2193.01  5010.6 2194.40  5015.6 2195.76  5020.8 2197.17  5027.9 2199.71
  5033.0 2199.66  5041.0 2200.54  5051.2 2202.36  5058.7 2203.38  5061.3 2203.38
#Mann=4,-1,0
  4810.2    0.16       0  4988.5    0.07       0  4992.5    0.16       0
  5015.6    0.07       0
Bank Sta=4988.5,4992.5
Exp/Cntr=0.3,0.1

Type RM Length L Ch R = 1,4925,497,497,497
BEGIN DESCRIPTION:
Bitter Creek Trib10T3 7.0
END DESCRIPTION:
XS GIS Cut Line= 3
      1413055.03      6829038.00      1413112.80      6829044.21
      1413305.00      6828938.00
#Sta/Elev= 30
  4941.9 2199.50  4944.4 2199.50  4951.9 2198.49  4962.0 2197.59  4972.0 2192.59
  4982.1 2189.44  4987.9 2188.74  4990.9 2188.72  4991.2 2188.22  4994.7 2188.22
  4994.9 2188.72  5005.4 2189.43  5021.4 2189.10  5027.1 2189.53  5043.2 2189.97
  5048.9 2190.74  5064.9 2192.03  5071.1 2192.01  5086.7 2193.82  5108.5 2195.09
  5116.8 2196.40  5124.5 2195.92  5130.2 2196.77  5146.3 2198.39  5152.0 2198.03
  5162.3 2198.77  5173.9 2200.10  5196.7 2200.62  5216.7 2202.14  5219.6 2202.14
#Mann=3,-1,0
  4941.9    0.07       0  4990.9    0.07       0  4994.9    0.07       0
Bank Sta=4990.9,4994.9
Exp/Cntr=0.3,0.1

Type RM Length L Ch R = 1,4428,497,497,497
BEGIN DESCRIPTION:
Bitter Creek Trib10T3 6.0
END DESCRIPTION:
XS GIS Cut Line= 3
      1413055.02      6829338.01      1413162.86      6829381.83
      1413304.97      6829437.99
#Sta/Elev= 30
  4883.6 2197.50  4886.3 2197.50  4892.9 2196.66  4898.3 2195.76  4905.2 2195.05
  4922.4 2194.80  4927.8 2193.93  4934.7 2192.45  4946.5 2189.69  4951.9 2188.66
  4981.3 2185.80  4991.5 2185.42  5003.4 2185.28  5003.7 2184.78  5007.2 2184.78
  5007.4 2185.28  5013.1 2185.28  5035.2 2185.84  5054.1 2186.96  5066.8 2189.04
  5077.6 2189.82  5083.9 2190.57  5108.2 2192.47  5113.6 2193.35  5120.6 2194.88
  5131.3 2195.03  5138.0 2196.65  5143.3 2196.04  5150.1 2197.49  5152.8 2197.49
#Mann=4,-1,0
  4883.6    0.16       0  4934.7    0.07       0  5003.4    0.07       0
  5007.4    0.07       0
Bank Sta=5003.4,5007.4
Exp/Cntr=0.3,0.1

Type RM Length L Ch R = 1,3931,497,497,497
BEGIN DESCRIPTION:
Bitter Creek Trib10T3 5.0
END DESCRIPTION:
XS GIS Cut Line= 3
      1412854.97      6829687.98      1412964.66      6829777.21
      1413005.03      6829838.04
#Sta/Elev= 30
  4858.6 2189.97  4861.9 2189.97  4872.3 2188.40  4880.2 2187.88  4894.6 2185.68
  4901.0 2183.86  4908.9 2183.77  4915.4 2182.27  4929.7 2181.80  4936.2 2180.68
  4944.1 2180.69  4950.6 2179.51  4958.5 2179.51  4966.7 2178.89  4972.8 2179.17
  4979.3 2177.03  4987.2 2177.02  4991.7 2176.38  4991.9 2175.88  4995.4 2175.88
  4995.7 2176.38  4997.0 2178.35  5003.5 2178.35  5008.3 2177.29  5029.3 2178.40
  5036.9 2179.25  5044.4 2181.10  5050.4 2181.70  5059.4 2185.89  5073.0 2187.00
#Mann=4,-1,0
  4858.6    0.16       0  4966.7    0.07       0  4991.7    0.07       0
  4995.7    0.07       0
Bank Sta=4991.7,4995.7
Exp/Cntr=0.3,0.1

Type RM Length L Ch R = 1,3434,497,497,497
BEGIN DESCRIPTION:
Bitter Creek Trib10T3 4.0
END DESCRIPTION:
XS GIS Cut Line= 3
      1412655.02      6830188.00      1412755.24      6830173.90
      1413054.97      6830038.01
#Sta/Elev= 30
  4898.8 2187.18  4929.1 2184.95  4934.4 2183.09  4959.4 2179.14  4989.7 2176.01
  4997.4 2174.50  5000.0 2174.50  5003.7 2175.92  5021.3 2169.26  5024.8 2169.20
  5025.0 2168.70  5028.5 2168.70  5028.8 2169.20  5032.7 2172.41  5049.9 2175.33
  5065.6 2177.01  5073.0 2179.09  5078.5 2178.49  5096.1 2180.60  5101.5 2180.15
  5109.5 2181.56  5131.5 2182.85  5193.9 2185.59  5222.5 2185.97  5240.1 2188.14
  5268.7 2187.99  5285.2 2190.26  5307.2 2191.46  5314.8 2192.54  5329.1 2192.68
#Mann=3,-1,0
  4898.8    0.07       0  5024.8    0.07       0  5028.8    0.07       0
Bank Sta=5024.8,5028.8
Exp/Cntr=0.3,0.1

Type RM Length L Ch R = 1,2937,498,498,498
BEGIN DESCRIPTION:
Bitter Creek Trib10T3 3.0
END DESCRIPTION:
XS GIS Cut Line= 3
      1412755.02      6830488.01      1412954.96      6830608.03
      1413105.00      6830638.00
#Sta/Elev= 30
  4766.8 2186.01  4790.1 2184.90  4801.8 2182.84  4825.1 2181.24  4854.2 2180.07
  4869.8 2177.66  4883.4 2174.47  4886.6 2173.16  4891.2 2171.28  4906.7 2168.81
  4912.5 2169.84  4928.1 2168.68  4933.9 2170.03  4949.5 2168.71  4968.8 2166.15
  4969.1 2165.65  4972.6 2165.65  4972.9 2166.15  4986.4 2166.70  5002.6 2166.41
  5010.2 2167.06  5020.3 2170.84  5025.4 2171.07  5030.6 2172.29  5061.2 2175.40
  5091.8 2179.85  5100.5 2180.53  5127.5 2181.80  5132.6 2182.75  5153.0 2184.55
#Mann=5,-1,0
  4766.8    0.07       0  4886.6    0.16       0  4968.8    0.07       0
  4972.9    0.16       0  5100.5    0.07       0
Bank Sta=4968.8,4972.9
Exp/Cntr=0.3,0.1

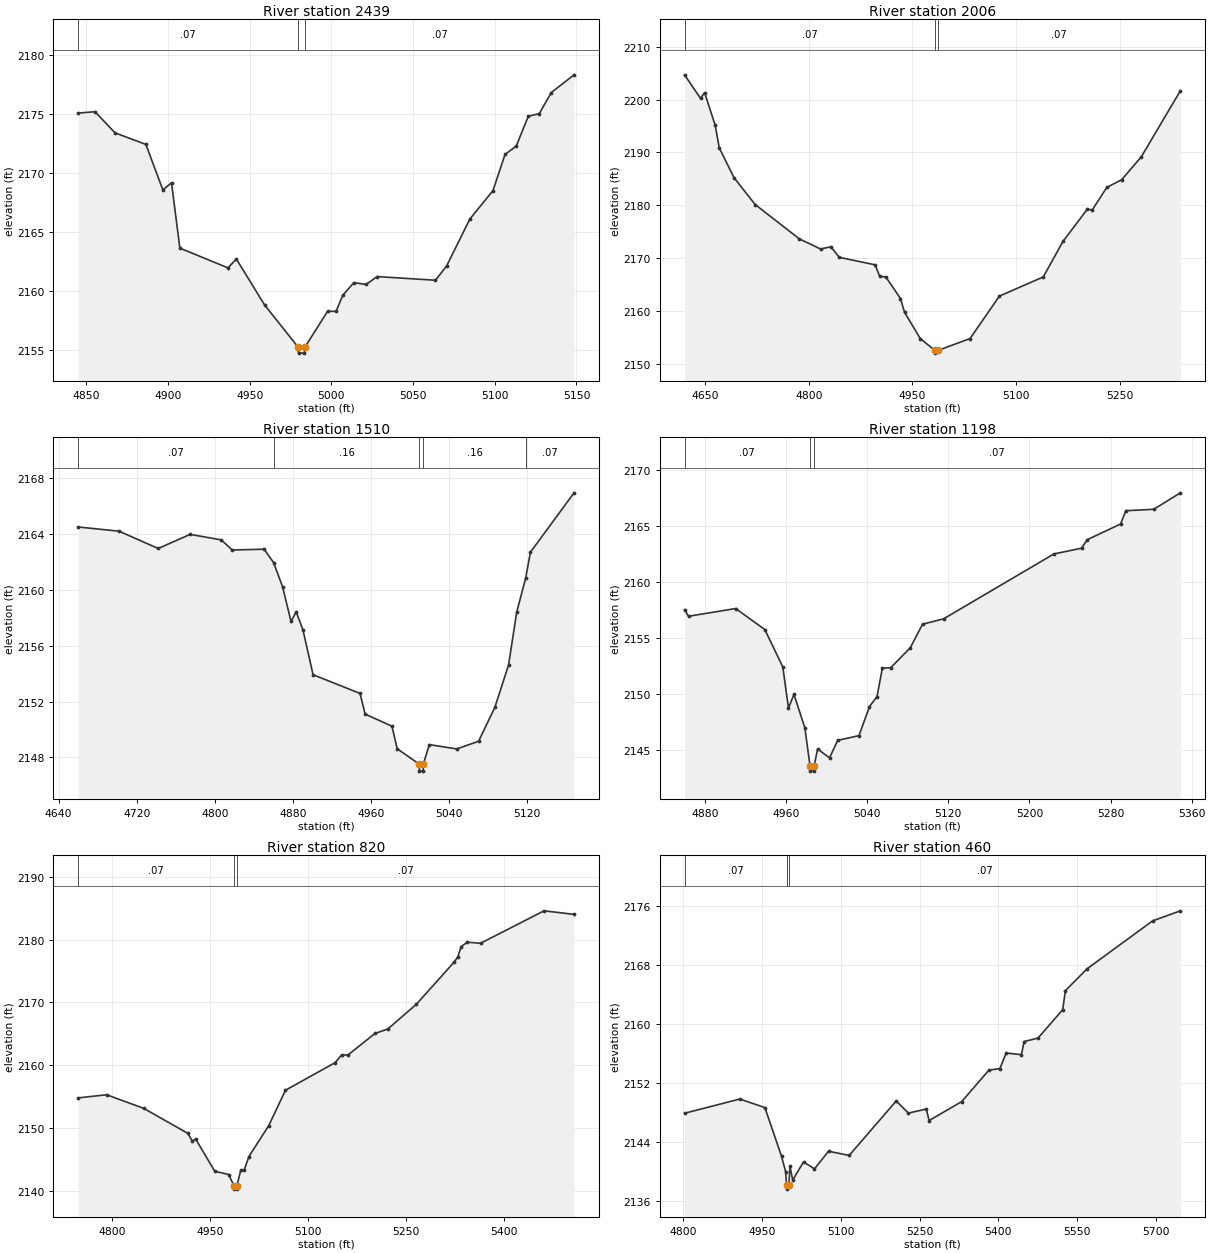
Type RM Length L Ch R = 1,2439,433,433,433
BEGIN DESCRIPTION:
Bitter Creek Trib10T3 2.0
END DESCRIPTION:
XS GIS Cut Line= 3
      1412605.01      6830738.02      1412645.66      6830887.49
      1412754.99      6830987.99
#Sta/Elev= 30
  4845.1 2175.07  4855.4 2175.19  4867.6 2173.40  4886.5 2172.42  4896.9 2168.57
  4902.2 2169.17  4907.3 2163.64  4936.7 2161.97  4941.9 2162.71  4959.1 2158.84
  4979.7 2155.25  4979.9 2154.75  4983.5 2154.75  4983.8 2155.25  4997.7 2158.29
  5002.9 2158.29  5007.0 2159.65  5013.8 2160.72  5021.2 2160.56  5028.0 2161.23
  5063.7 2160.92  5070.5 2162.12  5084.7 2166.09  5098.9 2168.51  5106.3 2171.58
  5113.1 2172.27  5120.5 2174.80  5127.2 2175.02  5134.6 2176.81  5148.5 2178.31
#Mann=3,-1,0
  4845.1    0.07       0  4979.7    0.07       0  4983.8    0.07       0
Bank Sta=4979.7,4983.8
Exp/Cntr=0.3,0.1

Type RM Length L Ch R = 1,2006,496,496,496
BEGIN DESCRIPTION:
Bitter Creek Trib10T3 1.0
END DESCRIPTION:
XS GIS Cut Line= 3
      1412154.98      6830837.97      1412354.99      6831160.72
      1412605.02      6831388.02
#Sta/Elev= 30
  4620.3 2204.70  4643.4 2200.24  4649.3 2201.34  4664.6 2195.16  4670.5 2190.89
  4691.8 2185.24  4722.5 2180.14  4786.3 2173.65  4817.1 2171.72  4832.1 2172.14
  4844.2 2170.14  4896.2 2168.72  4902.7 2166.54  4911.6 2166.43  4932.8 2162.34
  4938.7 2159.73  4961.5 2154.75  4982.8 2152.50  4983.0 2152.00  4986.9 2152.50
  5033.5 2154.76  5076.0 2162.80  5139.5 2166.43  5167.9 2173.14  5203.1 2179.23
  5210.5 2179.15  5231.4 2183.37  5253.1 2184.86  5281.4 2189.19  5337.9 2201.68
#Mann=3,-1,0
  4620.3    0.07       0  4982.8    0.07       0  4986.9    0.07       0
Bank Sta=4982.8,4986.9
Exp/Cntr=0.3,0.1

Type RM Length L Ch R = 1,1510,312,312,312
BEGIN DESCRIPTION:
Bitter Creek Trib10T3 0.1
END DESCRIPTION:
XS GIS Cut Line= 3
      1411954.99      6831187.95      1412054.73      6831512.89
      1412205.00      6831588.00
#Sta/Elev= 30
  4660.1 2164.52  4702.0 2164.22  4742.0 2162.98  4774.7 2163.99  4806.6 2163.60
  4817.9 2162.87  4850.6 2162.93  4860.2 2161.97  4869.4 2160.25  4878.1 2157.75
  4883.4 2158.43  4890.3 2157.15  4900.7 2153.93  4948.8 2152.59  4954.0 2151.11
  4981.5 2150.24  4986.8 2148.63  5009.4 2147.52  5009.7 2147.02  5013.3 2147.02
  5013.6 2147.52  5019.8 2148.92  5047.8 2148.61  5070.2 2149.16  5086.9 2151.59
  5100.9 2154.62  5109.3 2158.42  5118.4 2160.84  5123.3 2162.71  5168.0 2166.97
#Mann=5,-1,0
  4660.1    0.07       0  4860.2    0.16       0  5009.4    0.07       0
  5013.6    0.16       0  5118.4    0.07       0
Bank Sta=5009.4,5013.6
Exp/Cntr=0.3,0.1

Type RM Length L Ch R = 1,1198,378,378,378
BEGIN DESCRIPTION:
Bitter Creek Trib10T3 4278
END DESCRIPTION:
XS GIS Cut Line= 3
      1411876.42      6831751.46      1412004.54      6831808.17
      1412338.23      6831706.30
#Sta/Elev= 30
  4859.9 2157.54  4863.8 2156.95  4910.3 2157.64  4939.1 2155.76  4956.8 2152.42
  4962.4 2148.74  4967.8 2149.97  4978.6 2146.96  4983.6 2143.61  4983.9 2143.11
  4987.5 2143.11  4987.8 2143.61  4991.1 2145.10  5002.9 2144.29  5010.9 2145.86
  5031.9 2146.28  5042.3 2148.88  5049.7 2149.77  5055.0 2152.31  5063.2 2152.35
  5082.5 2154.13  5094.6 2156.24  5115.4 2156.72  5224.2 2162.52  5251.4 2163.03
  5257.0 2163.79  5289.9 2165.19  5295.1 2166.38  5322.7 2166.51  5348.9 2167.98
#Mann=3,-1,0
  4859.9    0.07       0  4983.6    0.07       0  4987.8    0.07       0
Bank Sta=4983.6,4987.8
Exp/Cntr=0.3,0.1

Type RM Length L Ch R = 1,820,360,360,360
BEGIN DESCRIPTION:
Bitter Creek Trib10T3 4279
END DESCRIPTION:
XS GIS Cut Line= 3
      1411963.16      6832046.58      1412205.42      6832113.00
      1412706.26      6832036.17
#Sta/Elev= 30
  4748.8 2154.77  4792.2 2155.27  4849.0 2153.10  4916.6 2149.10  4923.1 2147.87
  4928.3 2148.22  4957.5 2143.07  4978.8 2142.55  4987.1 2140.72  4987.3 2140.22
  4991.0 2140.22  4991.3 2140.72  4997.2 2143.20  5002.3 2143.20  5009.7 2145.42
  5040.0 2150.34  5065.6 2155.99  5141.2 2160.37  5151.3 2161.59  5161.4 2161.63
  5202.4 2165.04  5222.1 2165.76  5265.7 2169.70  5323.3 2176.41  5329.1 2177.25
  5334.1 2178.88  5343.5 2179.60  5363.8 2179.42  5460.8 2184.60  5506.7 2184.04
#Mann=3,-1,0
  4748.8    0.07       0  4987.1    0.07       0  4991.3    0.07       0
Bank Sta=4987.1,4991.3
Exp/Cntr=0.3,0.1

Type RM Length L Ch R = 1,460,156,156,156
BEGIN DESCRIPTION:
Bitter Creek Trib10T3 4280
END DESCRIPTION:
XS GIS Cut Line= 3
      1411820.82      6832327.83      1412007.07      6832393.86
      1412726.06      6832192.71
#Sta/Elev= 30
  4802.4 2147.93  4907.6 2149.86  4955.4 2148.70  4987.2 2142.07  4995.0 2139.97
  4996.6 2138.14  4996.9 2137.64  5000.9 2138.14  5003.1 2140.77  5008.3 2138.87
  5029.0 2141.33  5049.8 2140.39  5076.6 2142.78  5115.9 2142.21  5205.5 2149.60
  5228.7 2147.95  5262.8 2148.51  5268.0 2146.94  5330.1 2149.51  5382.1 2153.79
  5402.8 2153.98  5414.9 2156.10  5443.9 2155.88  5449.1 2157.66  5475.5 2158.13
  5522.5 2161.98  5527.7 2164.57  5569.0 2167.53  5693.6 2174.02  5746.6 2175.39
#Mann=3,-1,0
  4802.4    0.07       0  4996.6    0.07       0  5000.9    0.07       0
Bank Sta=4996.6,5000.9
Exp/Cntr=0.3,0.1

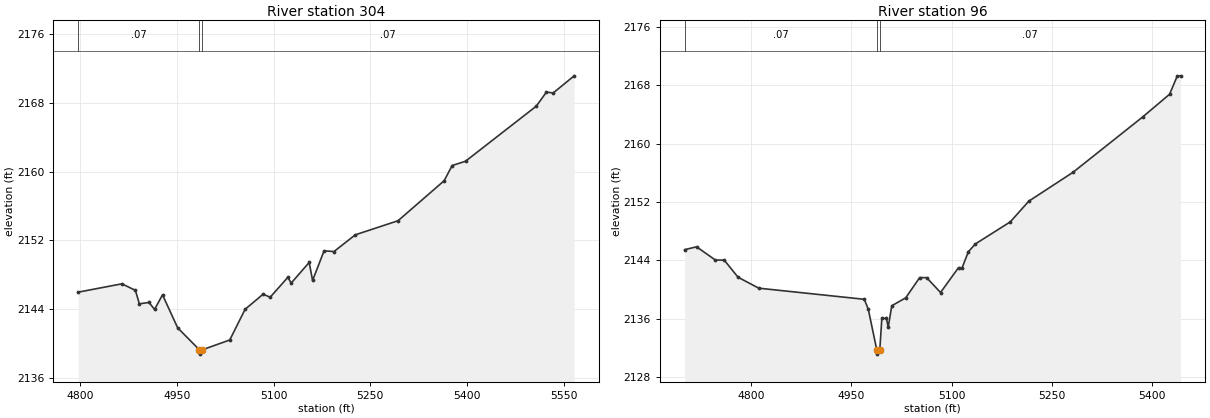
Type RM Length L Ch R = 1,304,208,208,208
BEGIN DESCRIPTION:
Bitter Creek Trib10T3 4281
END DESCRIPTION:
XS GIS Cut Line= 3
      1411827.78      6832432.01      1411994.14      6832547.64
      1412536.11      6832709.78
#Sta/Elev= 30
  4797.4 2145.95  4865.1 2146.92  4886.0 2146.16  4892.1 2144.59  4907.0 2144.75
  4915.7 2143.94  4928.0 2145.64  4951.5 2141.79  4985.2 2139.23  4985.5 2138.73
  4989.5 2139.23  5032.2 2140.38  5055.9 2143.95  5083.8 2145.71  5094.8 2145.36
  5122.1 2147.67  5127.4 2147.01  5155.2 2149.41  5160.5 2147.31  5178.3 2150.77
  5193.6 2150.68  5226.7 2152.63  5292.9 2154.27  5364.3 2158.93  5376.7 2160.70
  5397.4 2161.20  5507.1 2167.62  5522.8 2169.26  5533.2 2169.15  5565.7 2171.15
#Mann=3,-1,0
  4797.4    0.07       0  4985.2    0.07       0  4989.5    0.07       0
Bank Sta=4985.2,4989.5
Exp/Cntr=0.3,0.1

Type RM Length L Ch R = 1,96,0,0,0
BEGIN DESCRIPTION:
Bitter Creek Trib10T3 4460
END DESCRIPTION:
XS GIS Cut Line= 4
      1411837.77      6832470.77      1411879.44      6832629.63
      1411954.97      6832741.60      1412379.45      6832866.61
#Sta/Elev= 30
  4700.7 2145.48  4718.5 2145.87  4746.6 2144.06  4759.9 2144.05  4780.5 2141.71
  4811.6 2140.21  4969.4 2138.69  4975.4 2137.31  4988.2 2131.69  4988.5 2131.19
  4992.5 2131.69  4995.6 2136.09  5002.5 2136.09  5005.1 2134.86  5010.5 2137.81
  5031.3 2138.89  5052.2 2141.66  5062.6 2141.65  5083.4 2139.62  5110.3 2143.02
  5115.5 2142.96  5125.1 2145.21  5135.6 2146.27  5187.7 2149.28  5215.5 2152.12
  5281.5 2156.06  5385.7 2163.63  5426.0 2166.74  5437.6 2169.26  5442.5 2169.26
#Mann=3,-1,0
  4700.7    0.07       0  4988.2    0.07       0  4992.5    0.07       0
Bank Sta=4988.2,4992.5
Exp/Cntr=0.3,0.1

Chan Stop Cuts=-1