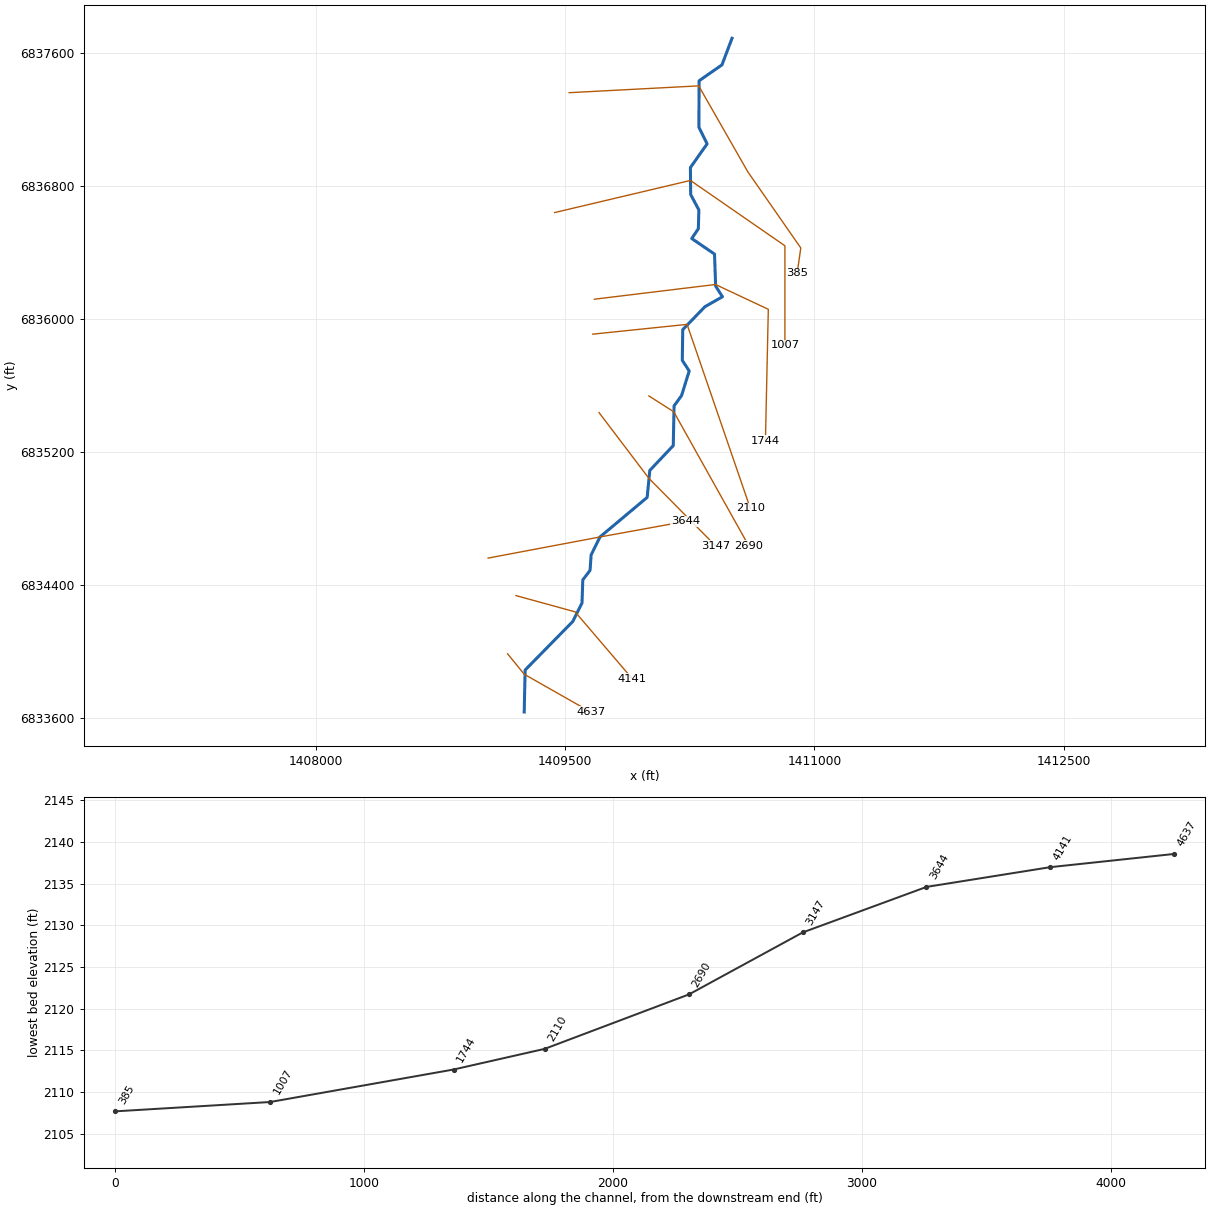
--- Bitter Creek Trib11.prj (project) ---

Proj Title=Bitter Creek Trib11 Base Level Engineering
Current Plan=p01
Default Exp/Contr=0.3,0.1
English Units
Geom File=g01
Flow File=f01
Plan File=p01
Y Axis Title=Elevation
X Axis Title(PF)=Main Channel Distance
X Axis Title(XS)=Station
BEGIN DESCRIPTION:
Bitter Creek Trib11
END DESCRIPTION:
DSS Export Rating Curves= 0
DSS Export Rating Curve Sorted= 0
DSS Export Volume Flow Curves= 0
DXF OffsetX= 0
DXF OffsetY= 0
DXF ScaleX= 1
DXF ScaleY= 10

--- Bitter Creek Trib11.p01 (plan) ---

Plan Title=Multiple Run
Short Identifier=Multiple
Geom File=g01
Flow File=f01
Subcritical Flow
K Sum by GR= 0
Std Step Tol= 0.01
Critical Tol= 0.01
Num of Std Step Trials= 20
Max Error Tol= 0.3
Flow Tol Ratio= 0.001
Split Flow NTrial= 30
Split Flow Tol= 0.02
Split Flow Ratio= 0.02
Log Output Level= 0
Friction Slope Method= 1
Unsteady Friction Slope Method= 2
Unsteady Bridges Friction Slope Method= 1
Parabolic Critical Depth
Global Vel Dist=  1 , 1 , 1
Global Log Level= 0
CheckData=True
Encroach Param= -1, 0, 0, 0
BEGIN DESCRIPTION:
Multiple Run
END DESCRIPTION:

--- Bitter Creek Trib11.f01 (steady flow) ---

Flow Title=Multiple
Number of Profiles=7
Profile Names=10-year,25-year,50-year,1pct_min,100-year,1pct_plu,500-year
River Rch & RM= Bitter Creek Tri,Reach-1,4637
     385     559     708     446     891    1777    1428
Boundary for River Rch & Prof#=Bitter Creek Tri,Reach-1,1
Up Type=0
Dn Type=3
Dn Slope=0.005
Boundary for River Rch & Prof#=Bitter Creek Tri,Reach-1,2
Up Type=0
Dn Type=3
Dn Slope=0.005
Boundary for River Rch & Prof#=Bitter Creek Tri,Reach-1,3
Up Type=0
Dn Type=3
Dn Slope=0.005
Boundary for River Rch & Prof#=Bitter Creek Tri,Reach-1,4
Up Type=0
Dn Type=3
Dn Slope=0.005
Boundary for River Rch & Prof#=Bitter Creek Tri,Reach-1,5
Up Type=0
Dn Type=3
Dn Slope=0.005
Boundary for River Rch & Prof#=Bitter Creek Tri,Reach-1,6
Up Type=0
Dn Type=3
Dn Slope=0.005
Boundary for River Rch & Prof#=Bitter Creek Tri,Reach-1,7
Up Type=0
Dn Type=3
Dn Slope=0.005

--- Bitter Creek Trib11.g01 (geometry) ---

Geom Title=Existing Conditions

River Reach=Bitter Creek Tri,Reach-1
Reach XY= 30
      1409255.00      6833638.00      1409260.46      6833890.45
      1409546.86      6834181.94      1409602.64      6834293.52
      1409607.39      6834432.47      1409651.14      6834489.60
      1409657.33      6834582.03      1409710.82      6834690.31
      1409994.52      6834928.20      1410010.47      6835090.45
      1410151.46      6835239.46      1410156.38      6835478.34
      1410201.15      6835539.60      1410247.44      6835688.00
      1410205.83      6835751.86      1410208.53      6835936.54
      1410341.82      6836074.37      1410447.31      6836134.33
      1410406.39      6836198.43      1410399.64      6836390.70
      1410262.69      6836484.33      1410302.42      6836543.44
      1410305.42      6836656.33      1410256.22      6836748.51
      1410254.63      6836910.88      1410355.04      6837053.34
      1410305.54      6837153.21      1410307.09      6837432.74
      1410444.38      6837527.99      1410505.00      6837688.00

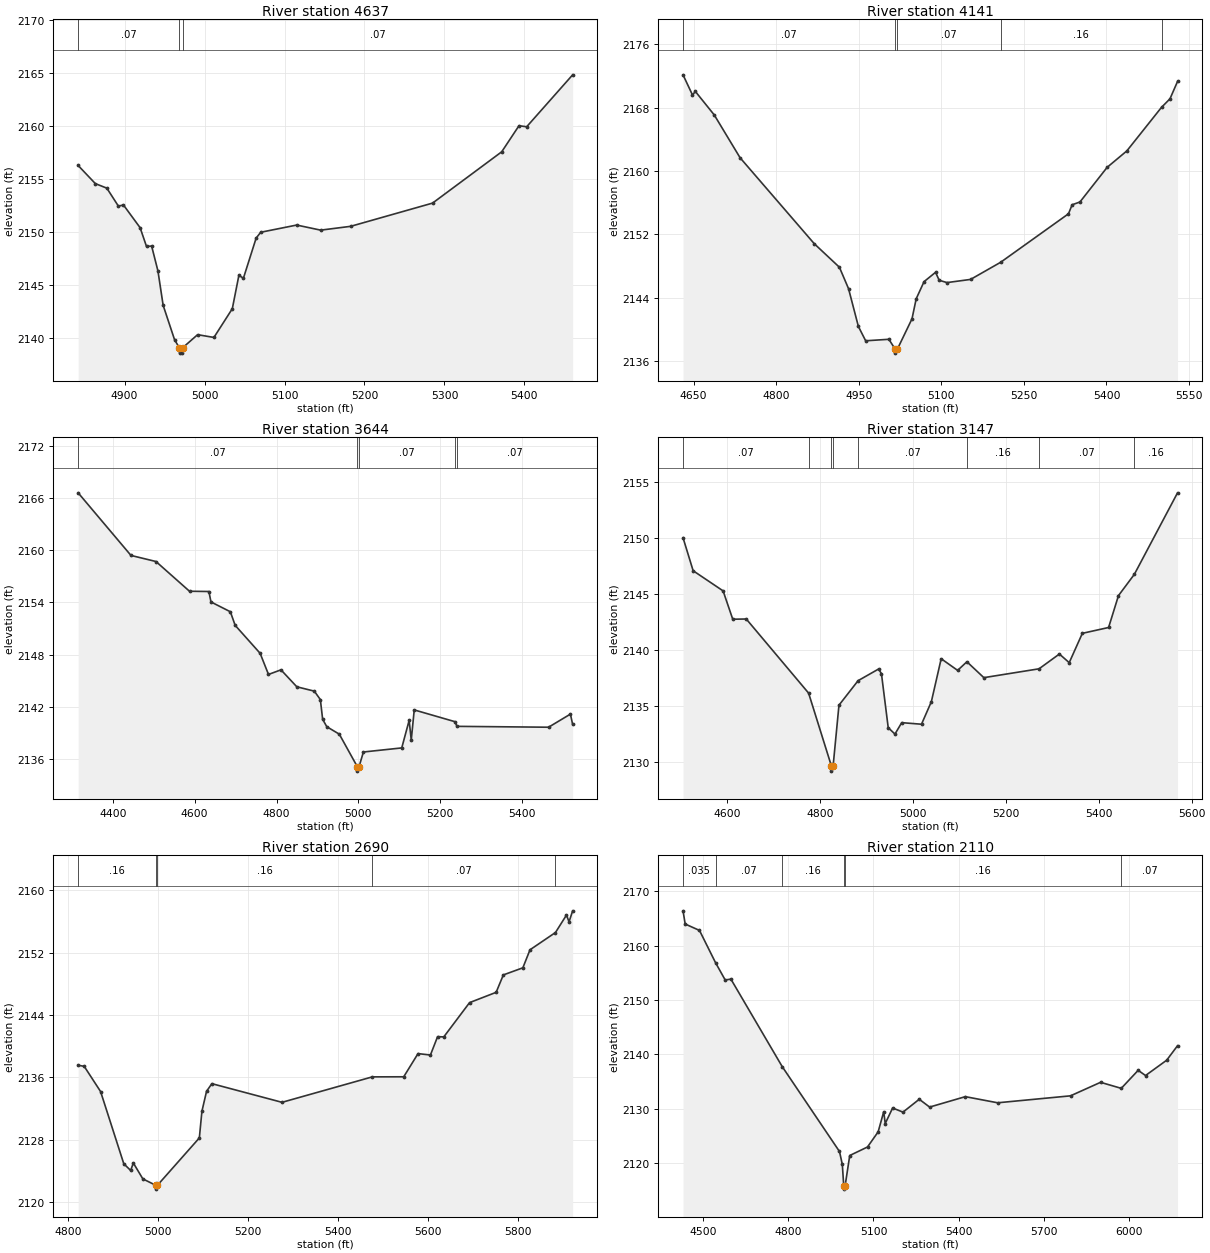
Type RM Length L Ch R = 1,4637,496,496,496
BEGIN DESCRIPTION:
Bitter Creek Trib11 5.0
END DESCRIPTION:
XS GIS Cut Line= 3
      1409155.01      6833987.98      1409254.80      6833865.36
      1409655.02      6833637.99
#Sta/Elev= 30
  4841.9 2156.25  4863.4 2154.54  4877.8 2154.11  4892.2 2152.42  4898.6 2152.52
  4919.4 2150.38  4927.4 2148.61  4933.8 2148.65  4941.7 2146.30  4948.2 2143.06
  4962.5 2139.81  4968.5 2139.05  4968.7 2138.55  4972.2 2138.55  4972.5 2139.05
  4991.3 2140.29  5011.7 2140.03  5034.7 2142.74  5042.9 2145.88  5048.6 2145.62
  5064.5 2149.40  5070.2 2149.95  5115.2 2150.63  5145.2 2150.15  5182.7 2150.51
  5285.1 2152.70  5371.6 2157.54  5393.2 2160.00  5402.8 2159.90  5460.3 2164.80
#Mann=3,-1,0
  4841.9    0.07       0  4968.5    0.07       0  4972.5    0.07       0
Bank Sta=4968.5,4972.5
Exp/Cntr=0.3,0.1

Type RM Length L Ch R = 1,4141,497,497,497
BEGIN DESCRIPTION:
Bitter Creek Trib11 4.0
END DESCRIPTION:
XS GIS Cut Line= 3
      1409205.03      6834337.99      1409561.14      6834240.17
      1409904.98      6833838.02
#Sta/Elev= 30
  4630.7 2172.16  4647.9 2169.61  4653.1 2170.06  4687.5 2167.08  4734.4 2161.67
  4869.2 2150.80  4914.8 2147.83  4931.4 2145.12  4949.3 2140.34  4962.5 2138.53
  5004.7 2138.72  5016.1 2137.47  5016.4 2136.97  5020.1 2137.47  5046.7 2141.31
  5054.3 2143.84  5068.6 2146.01  5089.5 2147.19  5096.1 2146.18  5110.3 2145.89
  5153.1 2146.29  5207.8 2148.46  5331.0 2154.59  5337.6 2155.73  5351.8 2156.08
  5401.2 2160.46  5437.0 2162.54  5500.0 2168.05  5515.4 2169.13  5529.1 2171.32
#Mann=5,-1,0
  4630.7    0.07       0  5016.1    0.07       0  5020.1    0.07       0
  5207.8    0.16       0  5500.0    0.07       0
Bank Sta=5016.1,5020.1
Exp/Cntr=0.3,0.1

Type RM Length L Ch R = 1,3644,497,497,497
BEGIN DESCRIPTION:
Bitter Creek Trib11 3.0
END DESCRIPTION:
XS GIS Cut Line= 3
      1409038.19      6834563.42      1409710.82      6834690.31
      1410225.69      6834783.90
#Sta/Elev= 30
  4315.5 2166.61  4444.5 2159.41  4505.6 2158.71  4587.5 2155.29  4634.9 2155.26
  4639.9 2154.06  4687.3 2152.93  4699.0 2151.37  4760.0 2148.15  4780.4 2145.72
  4810.9 2146.25  4849.6 2144.30  4892.3 2143.80  4907.1 2142.83  4912.7 2140.56
  4922.8 2139.71  4953.4 2138.85  4997.5 2135.10  4997.8 2134.60  5001.6 2135.10
  5012.2 2136.80  5105.9 2137.27  5124.0 2140.44  5129.1 2138.17  5136.4 2141.64
  5235.7 2140.29  5240.8 2139.75  5464.5 2139.65  5517.9 2141.16  5523.3 2139.97
#Mann=5,-1,0
  4315.5    0.07       0  4997.5    0.07       0  5001.6    0.07       0
  5235.7    0.16       0  5240.8    0.07       0
Bank Sta=4997.5,5001.6
Exp/Cntr=0.3,0.1

Type RM Length L Ch R = 1,3147,457,457,457
BEGIN DESCRIPTION:
Bitter Creek Trib11 2.0
END DESCRIPTION:
XS GIS Cut Line= 3
      1409705.01      6835437.98      1410004.58      6835043.17
      1410404.97      6834638.03
#Sta/Elev= 30
  4504.4 2149.99  4526.2 2147.04  4590.7 2145.24  4611.5 2142.71  4640.6 2142.73
  4774.9 2136.11  4823.7 2129.64  4823.9 2129.14  4827.8 2129.64  4840.3 2135.03
  4881.5 2137.22  4925.6 2138.26  4931.8 2137.85  4946.4 2133.02  4960.9 2132.45
  4975.5 2133.47  5018.1 2133.33  5039.3 2135.34  5060.5 2139.18  5095.9 2138.14
  5115.9 2138.91  5152.4 2137.49  5271.3 2138.28  5315.1 2139.60  5336.3 2138.83
  5364.6 2141.45  5421.1 2141.97  5442.4 2144.82  5476.6 2146.72  5569.6 2154.00
#Mann=8,-1,0
  4504.4    0.07       0  4774.9    0.16       0  4823.7    0.07       0
  4827.8    0.16       0  4881.5    0.07       0  5115.9    0.16       0
  5271.3    0.07       0  5476.6    0.16       0
Bank Sta=4823.7,4827.8
Exp/Cntr=0.3,0.1

Type RM Length L Ch R = 1,2690,580,580,580
BEGIN DESCRIPTION:
Bitter Creek Trib11 1.0
END DESCRIPTION:
XS GIS Cut Line= 3
      1410005.03      6835537.98      1410154.56      6835442.73
      1410604.99      6834638.01
#Sta/Elev= 30
  4822.7 2137.57  4836.2 2137.43  4872.6 2134.20  4924.2 2124.95  4939.5 2124.09
  4945.4 2125.05  4966.6 2123.01  4995.0 2122.20  4995.2 2121.70  4999.1 2122.20
  5092.2 2128.26  5097.9 2131.67  5108.2 2134.23  5120.0 2135.21  5276.0 2132.82
  5476.8 2136.08  5546.6 2136.09  5578.4 2139.06  5606.0 2138.88  5621.9 2141.23
  5635.7 2141.20  5693.0 2145.59  5752.1 2146.91  5768.1 2149.14  5811.5 2150.05
  5827.4 2152.36  5884.0 2154.57  5908.5 2156.81  5914.2 2155.94  5922.2 2157.35
#Mann=5,-1,0
  4822.7    0.16       0  4995.0    0.07       0  4999.1    0.16       0
  5476.8    0.07       0  5884.0    0.16       0
Bank Sta=4995,4999.1
Exp/Cntr=0.3,0.1

Type RM Length L Ch R = 1,2110,366,366,366
BEGIN DESCRIPTION:
Bitter Creek Trib11 4170
END DESCRIPTION:
XS GIS Cut Line= 3
      1409667.44      6835909.43      1410234.51      6835968.21
      1410615.03      6834861.92
#Sta/Elev= 30
  4429.9 2166.41  4437.5 2163.98  4487.8 2162.80  4544.3 2156.86  4578.2 2153.68
  4598.4 2153.83  4778.8 2137.73  4980.4 2122.09  4990.4 2119.72  4995.5 2115.66
  4995.8 2115.16  4999.9 2115.66  5016.5 2121.35  5079.0 2122.92  5116.5 2125.71
  5136.1 2129.42  5141.4 2127.24  5167.4 2130.10  5203.9 2129.34  5261.1 2131.71
  5297.6 2130.27  5423.2 2132.19  5536.9 2131.06  5793.3 2132.34  5899.1 2134.83
  5971.9 2133.72  6031.4 2137.04  6057.3 2136.08  6131.7 2138.90  6169.9 2141.57
#Mann=6,-1,0
  4429.9   0.035       0  4544.3    0.07       0  4778.8    0.16       0
  4995.5    0.07       0  4999.9    0.16       0  5971.9    0.07       0
Bank Sta=4995.5,4999.9
Exp/Cntr=0.3,0.1

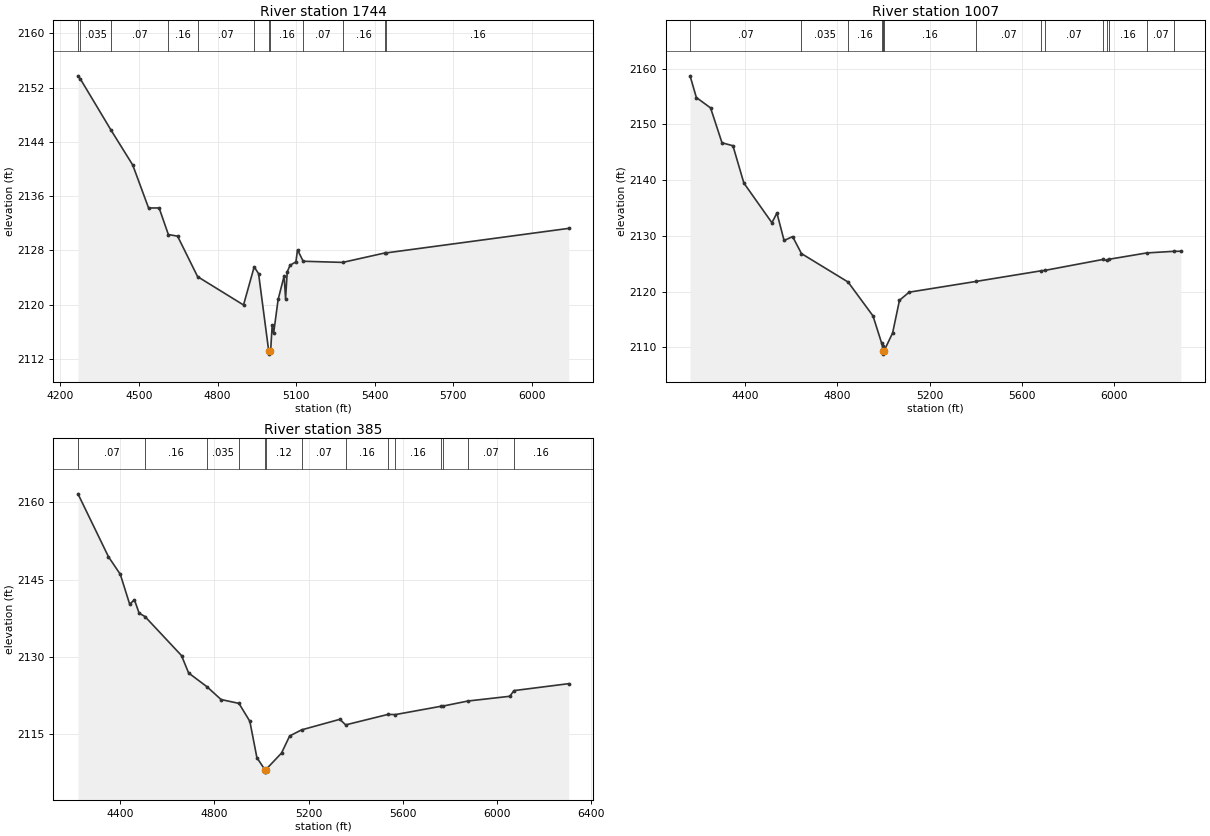
Type RM Length L Ch R = 1,1744,737,737,737
BEGIN DESCRIPTION:
Bitter Creek Trib11 4283
END DESCRIPTION:
XS GIS Cut Line= 4
      1409677.25      6836119.52      1410405.19      6836207.98
      1410723.23      6836058.76      1410705.87      6835268.85
#Sta/Elev= 30
  4266.7 2153.73  4275.9 2153.27  4392.4 2145.76  4476.0 2140.57  4536.4 2134.24
  4576.7 2134.24  4612.0 2130.32  4647.2 2130.08  4723.7 2124.11  4899.1 2119.93
  4939.8 2125.55  4956.6 2124.55  4995.2 2113.18  4995.5 2112.68  4999.6 2113.18
  5002.7 2113.18  5008.5 2116.95  5014.0 2115.74  5031.3 2120.74  5054.2 2124.21
  5059.7 2120.85  5066.1 2124.83  5077.0 2125.79  5099.2 2126.29  5105.3 2128.07
  5126.9 2126.38  5277.9 2126.21  5439.9 2127.61  5443.9 2127.61  6141.4 2131.23
#Mann=12,-1,0
  4266.7    0.07       0  4275.9   0.035       0  4392.4    0.07       0
  4612.0    0.16       0  4723.7    0.07       0  4939.8    0.16       0
  4995.2    0.07       0  4999.6    0.16       0  5126.9    0.07       0
  5277.9    0.16       0  5439.9    0.07       0  5443.9    0.16       0
Bank Sta=4995.2,4999.6
Exp/Cntr=0.3,0.1

Type RM Length L Ch R = 1,1007,622,622,622
BEGIN DESCRIPTION:
Bitter Creek Trib11 4284
END DESCRIPTION:
XS GIS Cut Line= 4
      1409438.47      6836640.34      1410254.84      6836833.44
      1410823.06      6836440.70      1410823.06      6835842.33
#Sta/Elev= 30
  4161.1 2158.69  4188.4 2154.80  4250.0 2152.94  4299.6 2146.68  4347.0 2146.15
  4394.4 2139.46  4516.1 2132.34  4537.7 2134.09  4568.7 2129.16  4605.8 2129.86
  4644.1 2126.81  4846.2 2121.71  4954.3 2115.63  4992.1 2110.70  4995.8 2110.17
  4996.8 2109.28  4997.1 2108.78  5001.3 2109.28  5039.3 2112.58  5069.1 2118.44
  5111.0 2119.89  5399.9 2121.81  5682.4 2123.72  5698.9 2123.79  5951.3 2125.76
  5967.4 2125.58  5978.6 2125.80  6141.4 2126.93  6259.5 2127.22  6289.1 2127.23
#Mann=15,-1,0
  4161.1    0.07       0  4644.1   0.035       0  4846.2    0.16       0
  4992.1    0.15       0  4995.8    0.16       0  4996.8    0.07       0
  5001.3    0.16       0  5399.9    0.07       0  5682.4    0.16       0
  5698.9    0.07       0  5951.3    0.16       0  5967.4    0.07       0
  5978.6    0.16       0  6141.4    0.07       0  6259.5    0.16       0
Bank Sta=4996.8,5001.3
Exp/Cntr=0.3,0.1

Type RM Length L Ch R = 1,385,0,0,0
BEGIN DESCRIPTION:
Bitter Creek Trib11 4285
END DESCRIPTION:
XS GIS Cut Line= 5
      1409525.36      6837360.84      1410304.48      6837401.90
      1410601.07      6836883.50      1410918.54      6836427.68
      1410896.84      6836275.75
#Sta/Elev= 30
  4219.8 2161.67  4349.6 2149.45  4399.7 2146.06  4439.7 2140.25  4459.8 2141.11
  4479.8 2138.51  4504.6 2137.86  4660.0 2130.28  4690.1 2126.91  4769.1 2124.20
  4828.1 2121.75  4904.2 2121.00  4950.5 2117.52  4980.5 2110.46  5014.1 2108.16
  5014.5 2107.66  5018.7 2108.16  5085.1 2111.36  5119.7 2114.68  5170.4 2115.86
  5333.1 2117.91  5357.8 2116.83  5537.6 2118.86  5569.2 2118.83  5763.1 2120.44
  5771.7 2120.48  5877.4 2121.46  6055.6 2122.38  6073.2 2123.48  6306.2 2124.83
#Mann=14,-1,0
  4219.8    0.07       0  4504.6    0.16       0  4769.1   0.035       0
  4904.2    0.12       0  5014.1    0.07       0  5018.7    0.12       0
  5170.4    0.07       0  5357.8    0.16       0  5537.6    0.07       0
  5569.2    0.16       0  5763.1    0.07       0  5771.7    0.16       0
  5877.4    0.07       0  6073.2    0.16       0
Bank Sta=5014.1,5018.7
Exp/Cntr=0.3,0.1

Chan Stop Cuts=-1