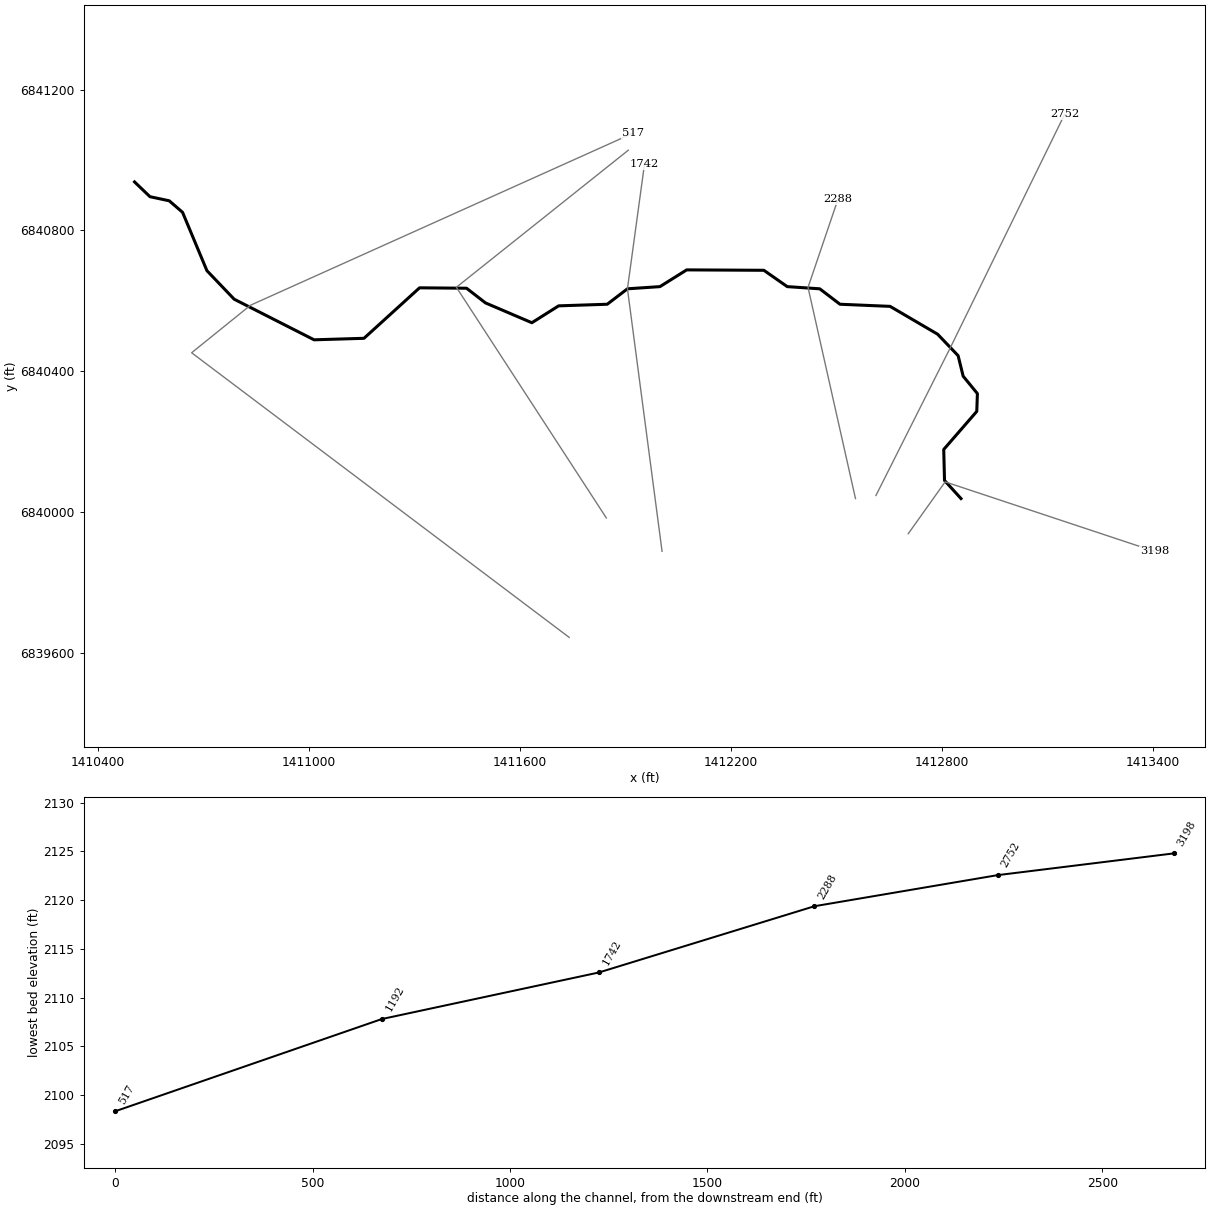
--- Bitter Creek Trib12.prj (project) ---

Proj Title=Bitter Creek Trib12 Base Level Engineering
Current Plan=p01
Default Exp/Contr=0.3,0.1
English Units
Geom File=g01
Flow File=f01
Plan File=p01
Y Axis Title=Elevation
X Axis Title(PF)=Main Channel Distance
X Axis Title(XS)=Station
BEGIN DESCRIPTION:
Bitter Creek Trib12
END DESCRIPTION:
DSS Export Rating Curves= 0
DSS Export Rating Curve Sorted= 0
DSS Export Volume Flow Curves= 0
DXF OffsetX= 0
DXF OffsetY= 0
DXF ScaleX= 1
DXF ScaleY= 10

--- Bitter Creek Trib12.p01 (plan) ---

Plan Title=Multiple Run
Short Identifier=Multiple
Geom File=g01
Flow File=f01
Subcritical Flow
K Sum by GR= 0
Std Step Tol= 0.01
Critical Tol= 0.01
Num of Std Step Trials= 20
Max Error Tol= 0.3
Flow Tol Ratio= 0.001
Split Flow NTrial= 30
Split Flow Tol= 0.02
Split Flow Ratio= 0.02
Log Output Level= 0
Friction Slope Method= 1
Unsteady Friction Slope Method= 2
Unsteady Bridges Friction Slope Method= 1
Parabolic Critical Depth
Global Vel Dist=  1 , 1 , 1
Global Log Level= 0
CheckData=True
Encroach Param= -1, 0, 0, 0
BEGIN DESCRIPTION:
Multiple Run
END DESCRIPTION:

--- Bitter Creek Trib12.f01 (steady flow) ---

Flow Title=Multiple
Number of Profiles=7
Profile Names=10-year,25-year,50-year,1pct_min,100-year,1pct_plu,500-year
River Rch & RM= Bitter Creek Tri,Reach-1,3198
     307     438     549     343     684    1365    1075
River Rch & RM= Bitter Creek Tri,Reach-1,2288
     347     498     627     392     782    1561    1234
Boundary for River Rch & Prof#=Bitter Creek Tri,Reach-1,1
Up Type=0
Dn Type=3
Dn Slope=0.005
Boundary for River Rch & Prof#=Bitter Creek Tri,Reach-1,2
Up Type=0
Dn Type=3
Dn Slope=0.005
Boundary for River Rch & Prof#=Bitter Creek Tri,Reach-1,3
Up Type=0
Dn Type=3
Dn Slope=0.005
Boundary for River Rch & Prof#=Bitter Creek Tri,Reach-1,4
Up Type=0
Dn Type=3
Dn Slope=0.005
Boundary for River Rch & Prof#=Bitter Creek Tri,Reach-1,5
Up Type=0
Dn Type=3
Dn Slope=0.005
Boundary for River Rch & Prof#=Bitter Creek Tri,Reach-1,6
Up Type=0
Dn Type=3
Dn Slope=0.005
Boundary for River Rch & Prof#=Bitter Creek Tri,Reach-1,7
Up Type=0
Dn Type=3
Dn Slope=0.005

--- Bitter Creek Trib12.g01 (geometry) ---

Geom Title=Existing Conditions

River Reach=Bitter Creek Tri,Reach-1
Reach XY= 30
      1412855.00      6840038.00      1412808.18      6840089.41
      1412805.93      6840177.53      1412899.90      6840285.71
      1412901.69      6840336.27      1412861.18      6840385.81
      1412846.87      6840444.07      1412788.58      6840505.08
      1412653.44      6840584.24      1412510.94      6840590.27
      1412453.40      6840634.14      1412360.98      6840640.36
      1412294.50      6840686.78      1412075.03      6840687.93
      1411999.02      6840640.36      1411906.60      6840634.14
      1411849.06      6840590.27      1411710.93      6840585.70
      1411634.82      6840537.71      1411502.82      6840594.11
      1411449.07      6840635.77      1411315.44      6840636.96
      1411157.45      6840493.45      1411015.50      6840489.19
      1410788.29      6840604.63      1410710.83      6840685.69
      1410641.54      6840851.57      1410603.66      6840884.29
      1410548.89      6840895.95      1410505.00      6840938.00

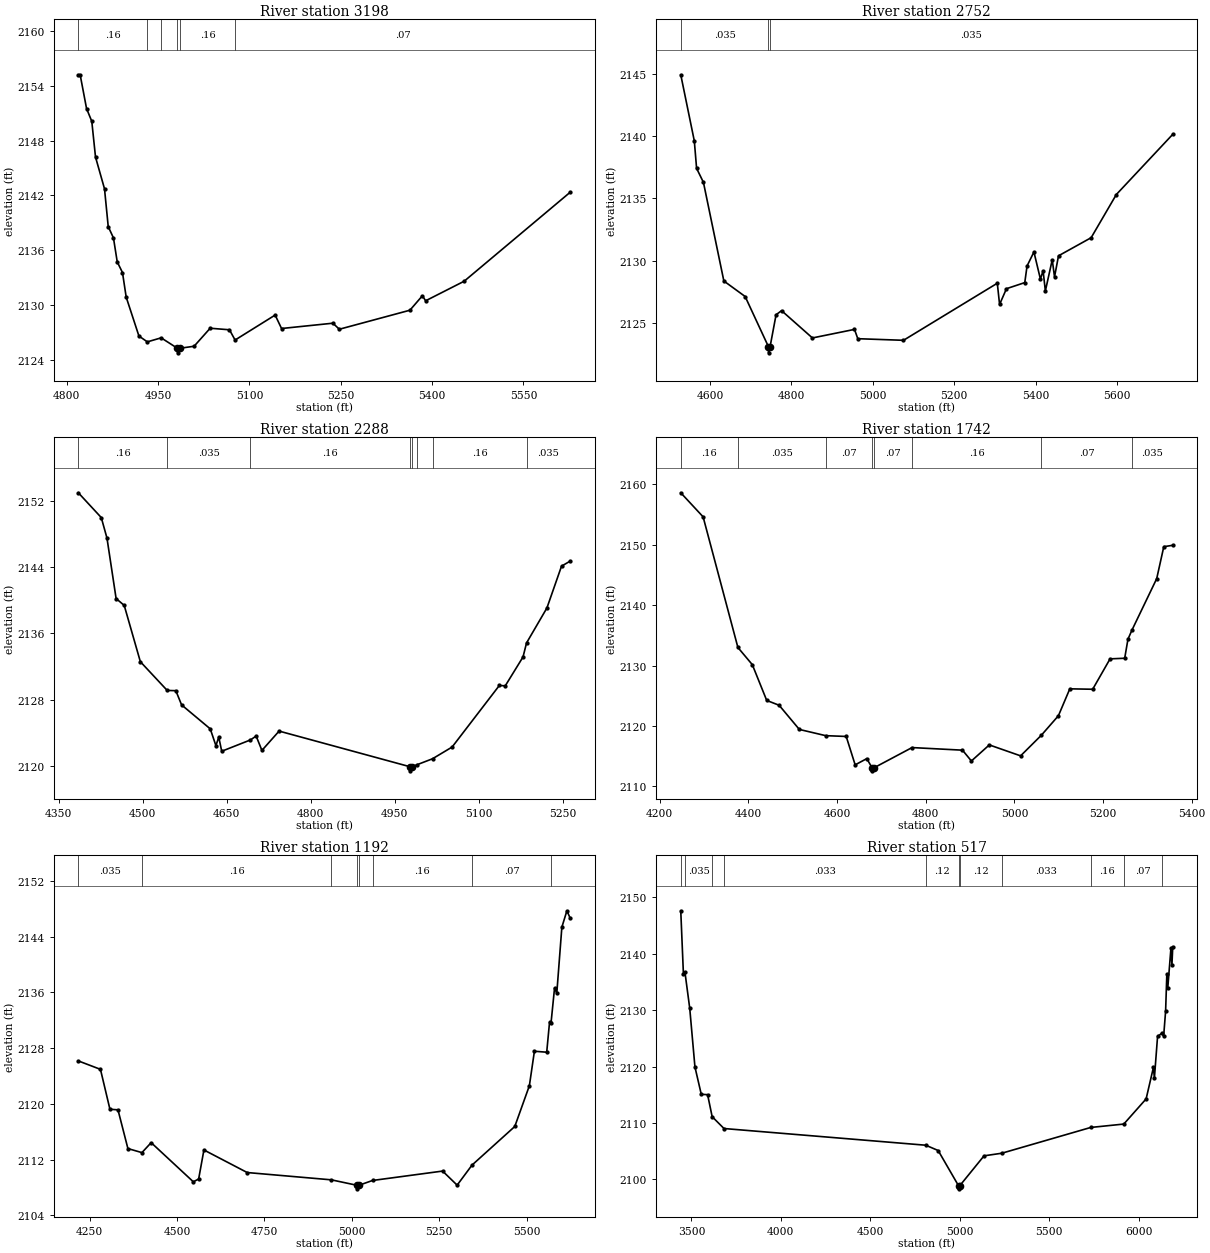
Type RM Length L Ch R = 1,3198,446,446,446
BEGIN DESCRIPTION:
Bitter Creek Trib12 2.0
END DESCRIPTION:
XS GIS Cut Line= 3
      1412705.03      6839938.04      1412810.05      6840085.45
      1413405.04      6839887.99
#Sta/Elev= 30
  4819.0 2155.19  4822.0 2155.19  4832.5 2151.50  4841.1 2150.10  4847.2 2146.20
  4862.0 2142.72  4868.1 2138.59  4876.7 2137.35  4882.9 2134.73  4891.5 2133.57
  4897.6 2130.88  4918.5 2126.63  4932.3 2125.99  4955.0 2126.43  4981.7 2125.29
  4981.9 2124.79  4985.7 2125.29  5009.1 2125.51  5035.5 2127.48  5067.2 2127.31
  5076.4 2126.19  5142.2 2128.92  5152.7 2127.45  5237.0 2128.03  5247.6 2127.37
  5363.5 2129.45  5384.0 2131.03  5389.3 2130.48  5452.6 2132.62  5626.9 2142.36
#Mann=6,-1,0
  4819.0    0.16       0  4932.3   0.035       0  4955.0    0.16       0
  4981.7    0.07       0  4985.7    0.16       0  5076.4    0.07       0
Bank Sta=4981.7,4985.7
Exp/Cntr=0.3,0.1

Type RM Length L Ch R = 1,2752,464,464,464
BEGIN DESCRIPTION:
Bitter Creek Trib12 4167
END DESCRIPTION:
XS GIS Cut Line= 3
      1412613.24      6840046.73      1412825.42      6840468.24
      1413149.69      6841130.06
#Sta/Elev= 30
  4528.1 2144.97  4561.4 2139.64  4567.0 2137.43  4583.8 2136.30  4634.0 2128.35
  4686.3 2127.10  4743.5 2123.06  4743.8 2122.56  4747.6 2123.06  4762.3 2125.63
  4775.8 2125.96  4851.6 2123.76  4955.0 2124.45  4963.1 2123.70  5075.4 2123.57
  5305.9 2128.17  5311.5 2126.46  5328.4 2127.73  5373.4 2128.22  5379.0 2129.56
  5395.9 2130.69  5411.8 2128.51  5418.4 2129.17  5424.0 2127.55  5440.9 2130.06
  5446.5 2128.68  5456.3 2130.38  5536.5 2131.84  5598.4 2135.32  5737.0 2140.17
#Mann=3,-1,0
  4528.1   0.035       0  4743.5   0.035       0  4747.6   0.035       0
Bank Sta=4743.5,4747.6
Exp/Cntr=0.3,0.1

Type RM Length L Ch R = 1,2288,546,546,546
BEGIN DESCRIPTION:
Bitter Creek Trib12 1.0
END DESCRIPTION:
XS GIS Cut Line= 3
      1412554.99      6840038.03      1412420.06      6840638.15
      1412505.00      6840888.01
#Sta/Elev= 30
  4384.9 2153.02  4425.9 2150.02  4436.1 2147.53  4452.4 2140.22  4466.9 2139.39
  4495.7 2132.58  4543.7 2129.10  4559.1 2129.07  4569.4 2127.35  4620.6 2124.45
  4630.7 2122.42  4635.8 2123.45  4641.1 2121.74  4692.4 2123.11  4702.6 2123.58
  4712.9 2121.84  4743.6 2124.18  4977.3 2119.87  4977.5 2119.37  4981.4 2119.87
  4990.4 2120.12  5017.7 2120.83  5052.7 2122.25  5137.1 2129.70  5147.7 2129.66
  5179.4 2133.15  5185.7 2134.85  5222.1 2139.08  5248.2 2144.14  5263.9 2144.76
#Mann=8,-1,0
  4384.9    0.16       0  4543.7   0.035       0  4692.4    0.16       0
  4977.3   0.035       0  4981.4    0.16       0  4990.4   0.035       0
  5017.7    0.16       0  5185.7   0.035       0
Bank Sta=4977.3,4981.4
Exp/Cntr=0.3,0.1

Type RM Length L Ch R = 1,1742,550,550,550
BEGIN DESCRIPTION:
Bitter Creek Trib12 0.1
END DESCRIPTION:
XS GIS Cut Line= 3
      1412005.00      6839888.00      1411906.60      6840634.14
      1411955.01      6840988.05
#Sta/Elev= 30
  4247.4 2158.58  4297.8 2154.60  4376.3 2132.98  4408.8 2130.14  4441.3 2124.22
  4469.3 2123.42  4514.9 2119.42  4574.4 2118.39  4620.6 2118.26  4640.8 2113.56
  4667.0 2114.59  4679.0 2113.07  4679.3 2112.57  4683.2 2113.07  4769.1 2116.42
  4882.9 2115.99  4903.0 2114.20  4943.4 2116.86  5014.0 2115.05  5060.8 2118.46
  5099.3 2121.69  5125.0 2126.14  5176.6 2126.07  5215.8 2131.10  5248.8 2131.20
  5256.2 2134.36  5265.4 2135.89  5321.0 2144.37  5337.0 2149.66  5357.2 2149.89
#Mann=8,-1,0
  4247.4    0.16       0  4376.3   0.035       0  4574.4    0.07       0
  4679.0    0.07       0  4683.2    0.07       0  4769.1    0.16       0
  5060.8    0.07       0  5265.4   0.035       0
Bank Sta=4679,4683.2
Exp/Cntr=0.3,0.1

Type RM Length L Ch R = 1,1192,675,675,675
BEGIN DESCRIPTION:
Bitter Creek Trib12 4170
END DESCRIPTION:
XS GIS Cut Line= 3
      1411846.50      6839982.92      1411420.16      6840638.48
      1411909.01      6841028.07
#Sta/Elev= 30
  4218.0 2126.15  4281.3 2124.94  4308.4 2119.21  4331.4 2119.13  4359.8 2113.57
  4399.9 2112.99  4426.3 2114.42  4546.9 2108.80  4562.1 2109.20  4577.2 2113.37
  4701.0 2110.13  4942.0 2109.08  5015.8 2108.29  5016.1 2107.79  5020.0 2108.29
  5059.4 2108.99  5259.8 2110.34  5301.4 2108.32  5344.0 2111.20  5466.3 2116.74
  5508.0 2122.59  5522.4 2127.54  5557.6 2127.40  5565.6 2131.67  5570.0 2131.62
  5580.0 2136.61  5586.4 2135.86  5600.9 2145.34  5615.3 2147.70  5625.1 2146.60
#Mann=8,-1,0
  4218.0   0.035       0  4399.9    0.16       0  4942.0   0.033       0
  5015.8   0.033       0  5020.0   0.033       0  5059.4    0.16       0
  5344.0    0.07       0  5570.0   0.035       0
Bank Sta=5015.8,5020
Exp/Cntr=0.3,0.1

Type RM Length L Ch R = 1,517,0,0,0
BEGIN DESCRIPTION:
Bitter Creek Trib12 4171
END DESCRIPTION:
XS GIS Cut Line= 4
      1411740.90      6839643.40      1410667.35      6840452.39
      1410834.79      6840587.51      1411921.44      6841076.02
#Sta/Elev= 30
  3440.6 2147.61  3455.4 2136.43  3464.2 2136.68  3490.8 2130.32  3519.9 2119.93
  3555.3 2115.08  3590.7 2115.02  3616.1 2111.12  3682.2 2109.02  4810.7 2106.06
  4879.8 2105.12  4994.6 2098.83  4995.0 2098.33  4999.2 2098.83  5136.3 2104.18
  5235.3 2104.64  5733.1 2109.21  5917.7 2109.81  6042.5 2114.27  6083.3 2119.84
  6088.8 2117.97  6106.5 2125.34  6128.8 2125.87  6140.6 2125.41  6151.5 2129.84
  6158.3 2136.32  6163.8 2134.01  6181.5 2141.06  6186.9 2138.08  6191.4 2141.23
#Mann=11,-1,0
  3440.6    0.16       0  3464.2   0.035       0  3616.1    0.16       0
  3682.2   0.033       0  4810.7    0.12       0  4994.6    0.07       0
  4999.2    0.12       0  5235.3   0.033       0  5733.1    0.16       0
  5917.7    0.07       0  6128.8   0.035       0
Bank Sta=4994.6,4999.2
Exp/Cntr=0.3,0.1

Chan Stop Cuts=-1