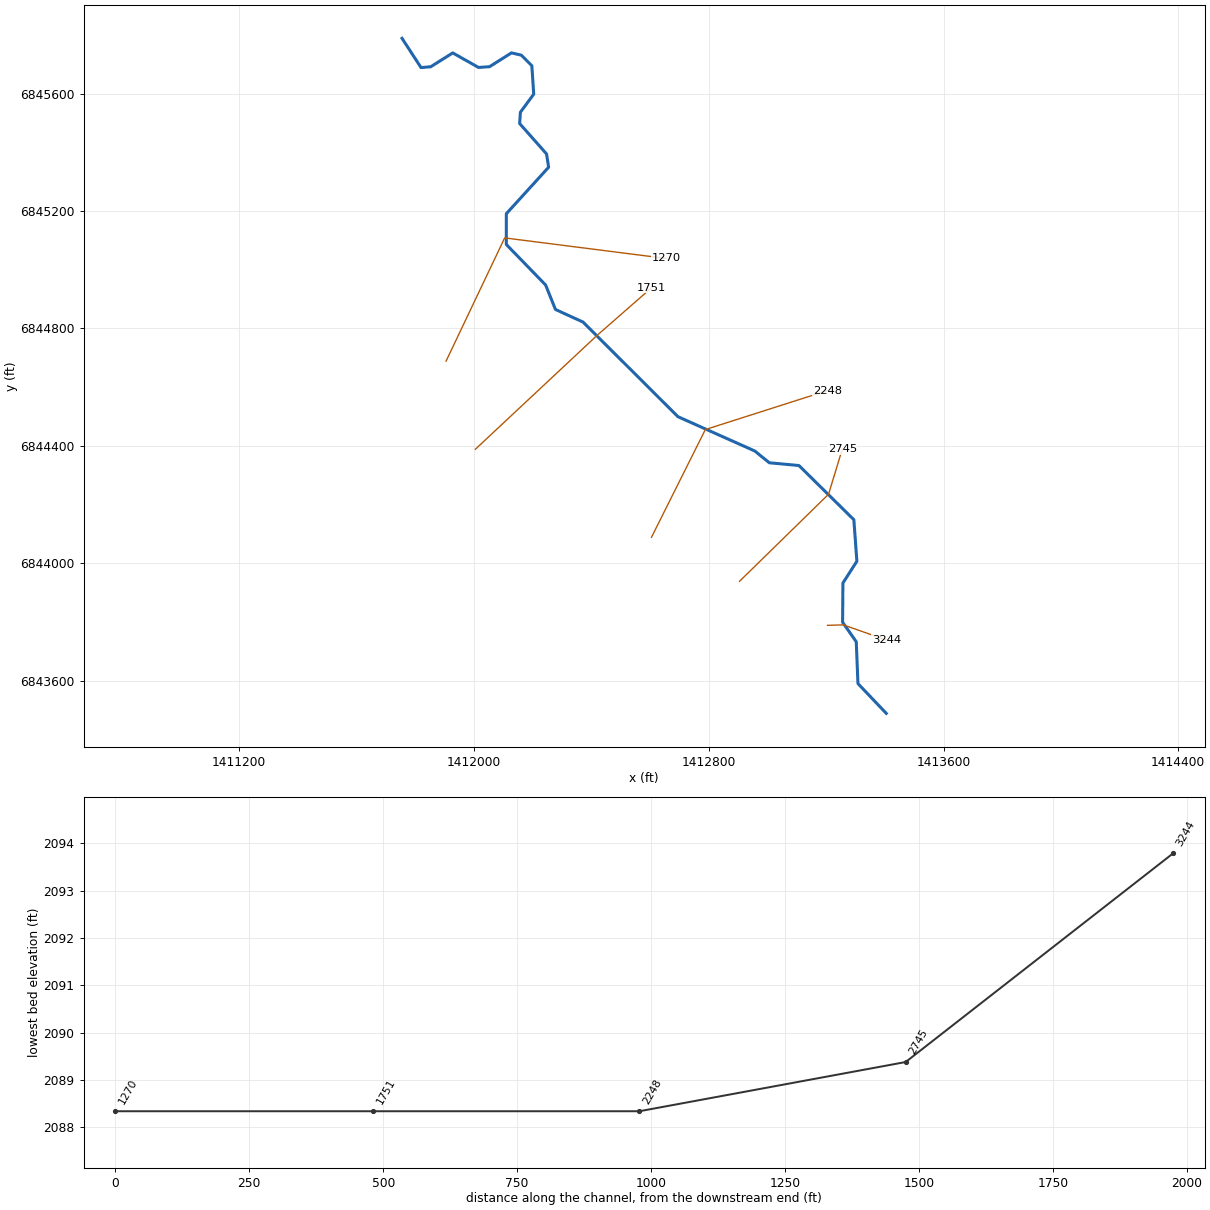
--- Bitter Creek Trib13.prj (project) ---

Proj Title=Bitter Creek Trib13 Base Level Engineering
Current Plan=p01
Default Exp/Contr=0.3,0.1
English Units
Geom File=g01
Flow File=f01
Plan File=p01
BEGIN DESCRIPTION:
Bitter Creek Trib13
END DESCRIPTION:

--- Bitter Creek Trib13.p01 (plan) ---

Plan Title=Multiple Run
Short Identifier=Multiple
Geom File=g01
Flow File=f01
Subcritical Flow
K Sum by GR= 0
Std Step Tol= 0.01
Critical Tol= 0.01
Num of Std Step Trials= 20
Max Error Tol= 0.3
Flow Tol Ratio= 0.001
Split Flow NTrial= 30
Split Flow Tol= 0.02
Split Flow Ratio= 0.02
Log Output Level= 0
Friction Slope Method= 1
Unsteady Friction Slope Method= 2
Unsteady Bridges Friction Slope Method= 1
Parabolic Critical Depth
Global Vel Dist=  1 , 1 , 1
Global Log Level= 0
CheckData=True
Encroach Param= -1, 0, 0, 0
BEGIN DESCRIPTION:
Multiple Run
END DESCRIPTION:

--- Bitter Creek Trib13.f01 (steady flow) ---

Flow Title=Multiple
Number of Profiles=7
Profile Names=10-year,25-year,50-year,1pct_min,100-year,1pct_plu,500-year
River Rch & RM= Bitter Creek Tri,Reach-1,3244
     427     629     807     515    1028    2050    1688
River Rch & RM= Bitter Creek Tri,Reach-1,2745
     420     615     785     499     995    1985    1618
Boundary for River Rch & Prof#=Bitter Creek Tri,Reach-1,1
Up Type=0
Dn Type=3
Dn Slope=0.005
Boundary for River Rch & Prof#=Bitter Creek Tri,Reach-1,2
Up Type=0
Dn Type=3
Dn Slope=0.005
Boundary for River Rch & Prof#=Bitter Creek Tri,Reach-1,3
Up Type=0
Dn Type=3
Dn Slope=0.005
Boundary for River Rch & Prof#=Bitter Creek Tri,Reach-1,4
Up Type=0
Dn Type=3
Dn Slope=0.005
Boundary for River Rch & Prof#=Bitter Creek Tri,Reach-1,5
Up Type=0
Dn Type=3
Dn Slope=0.005
Boundary for River Rch & Prof#=Bitter Creek Tri,Reach-1,6
Up Type=0
Dn Type=3
Dn Slope=0.005
Boundary for River Rch & Prof#=Bitter Creek Tri,Reach-1,7
Up Type=0
Dn Type=3
Dn Slope=0.005

--- Bitter Creek Trib13.g01 (geometry) ---

Geom Title=Existing Conditions

River Reach=Bitter Creek Tri,Reach-1
Reach XY= 30
      1413405.00      6843488.00      1413308.49      6843589.45
      1413302.73      6843732.06      1413256.21      6843798.51
      1413257.25      6843932.06      1413304.81      6844006.28
      1413294.53      6844147.80      1413107.43      6844332.48
      1413006.59      6844341.83      1412957.18      6844381.88
      1412695.32      6844498.76      1412371.66      6844821.34
      1412277.86      6844864.16      1412244.21      6844947.66
      1412110.40      6845085.57      1412110.40      6845190.43
      1412254.45      6845348.64      1412247.52      6845394.04
      1412155.76      6845497.78      1412158.34      6845536.25
      1412203.72      6845597.71      1412197.36      6845694.55
      1412161.39      6845730.65      1412127.92      6845738.49
      1412053.28      6845691.41      1412015.69      6845688.79
      1411927.79      6845738.36      1411852.91      6845691.21
      1411819.81      6845688.34      1411755.00      6845788.00

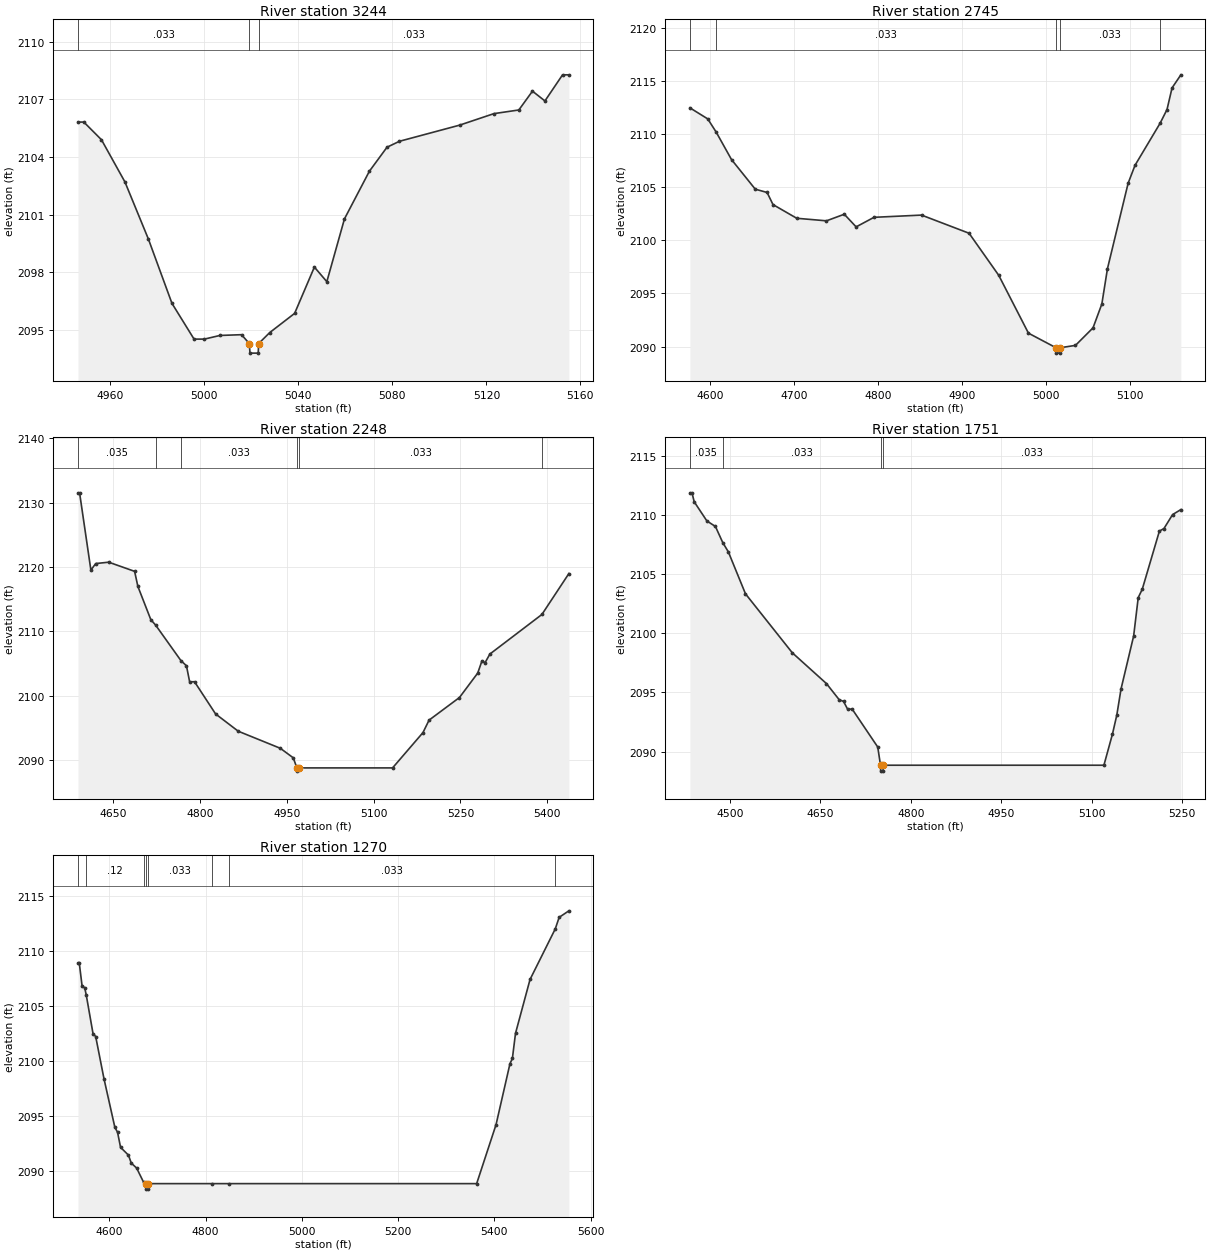
Type RM Length L Ch R = 1,3244,499,499,499
BEGIN DESCRIPTION:
Bitter Creek Trib13 4.0
END DESCRIPTION:
XS GIS Cut Line= 3
      1413205.00      6843788.00      1413258.77      6843789.57
      1413405.04      6843737.98
#Sta/Elev= 29
  4946.2 2105.82  4948.7 2105.82  4956.2 2104.90  4966.2 2102.70  4976.2 2099.72
  4986.2 2096.38  4995.6 2094.52  5000.0 2094.52  5006.6 2094.71  5015.8 2094.75
  5019.1 2094.29  5019.4 2093.79  5022.9 2093.79  5023.1 2094.29  5027.8 2094.86
  5038.4 2095.86  5046.8 2098.27  5052.1 2097.51  5059.6 2100.78  5070.2 2103.26
  5077.7 2104.51  5083.0 2104.82  5108.6 2105.66  5123.2 2106.26  5133.8 2106.45
  5139.6 2107.43  5144.9 2106.92  5152.4 2108.28  5155.1 2108.28
#Mann=3,-1,0
  4946.2   0.033       0  5019.1   0.033       0  5023.1   0.033       0
Bank Sta=5019.1,5023.1
Exp/Cntr=0.3,0.1

Type RM Length L Ch R = 1,2745,497,497,497
BEGIN DESCRIPTION:
Bitter Creek Trib13 3.0
END DESCRIPTION:
XS GIS Cut Line= 3
      1412905.01      6843938.01      1413208.35      6844234.68
      1413255.01      6844388.04
#Sta/Elev= 30
  4575.7 2112.48  4596.9 2111.44  4607.0 2110.19  4625.2 2107.61  4653.5 2104.82
  4667.6 2104.51  4674.6 2103.37  4702.9 2102.08  4738.3 2101.84  4759.5 2102.46
  4773.6 2101.27  4794.9 2102.17  4851.5 2102.38  4908.1 2100.67  4943.4 2096.71
  4978.8 2091.26  5011.8 2089.88  5012.1 2089.38  5015.8 2089.38  5016.1 2089.88
  5034.8 2090.11  5055.7 2091.76  5066.2 2094.01  5072.9 2097.34  5097.5 2105.38
  5105.7 2107.07  5135.5 2111.02  5143.8 2112.32  5149.8 2114.36  5160.3 2115.59
#Mann=5,-1,0
  4575.7   0.035       0  4607.0   0.033       0  5011.8   0.033       0
  5016.1   0.033       0  5135.5   0.035       0
Bank Sta=5011.8,5016.1
Exp/Cntr=0.3,0.1

Type RM Length L Ch R = 1,2248,497,497,497
BEGIN DESCRIPTION:
Bitter Creek Trib13 2.0
END DESCRIPTION:
XS GIS Cut Line= 3
      1412605.01      6844088.02      1412788.48      6844455.02
      1413204.97      6844587.99
#Sta/Elev= 30
  4589.7 2131.51  4592.5 2131.51  4612.0 2119.53  4620.4 2120.54  4642.8 2120.75
  4687.5 2119.33  4693.1 2117.00  4715.5 2111.83  4723.7 2111.00  4767.4 2105.49
  4777.0 2104.68  4782.5 2102.19  4790.9 2102.21  4827.3 2097.21  4866.4 2094.53
  4939.1 2091.88  4961.4 2090.40  4967.6 2088.84  4967.9 2088.34  4972.0 2088.84
  5132.8 2088.84  5185.3 2094.32  5195.8 2096.25  5248.3 2099.76  5279.8 2103.55
  5287.2 2105.46  5292.4 2105.15  5300.8 2106.50  5390.6 2112.64  5437.2 2118.99
#Mann=6,-1,0
  4589.7   0.035       0  4723.7    0.07       0  4767.4   0.033       0
  4967.6   0.033       0  4972.0   0.033       0  5390.6   0.035       0
Bank Sta=4967.6,4972
Exp/Cntr=0.3,0.1

Type RM Length L Ch R = 1,1751,481,481,481
BEGIN DESCRIPTION:
Bitter Creek Trib13 1.0
END DESCRIPTION:
XS GIS Cut Line= 3
      1412005.00      6844388.00      1412418.38      6844774.77
      1412604.98      6844937.98
#Sta/Elev= 30
  4433.9 2111.90  4437.3 2111.90  4441.0 2111.14  4462.0 2109.52  4476.2 2109.05
  4488.3 2107.69  4497.6 2106.90  4526.0 2103.35  4603.6 2098.36  4660.3 2095.75
  4681.3 2094.39  4688.6 2094.24  4695.5 2093.57  4702.8 2093.60  4745.3 2090.38
  4749.9 2088.84  4750.2 2088.34  4754.1 2088.34  4754.4 2088.84  5120.3 2088.84
  5134.5 2091.48  5141.7 2093.09  5148.7 2095.30  5169.6 2099.78  5177.2 2103.03
  5183.9 2103.74  5212.3 2108.66  5219.9 2108.88  5234.2 2110.06  5247.9 2110.48
#Mann=4,-1,0
  4433.9   0.035       0  4488.3   0.033       0  4749.9   0.033       0
  4754.4   0.033       0
Bank Sta=4749.9,4754.4
Exp/Cntr=0.3,0.1

Type RM Length L Ch R = 1,1270,0,0,0
BEGIN DESCRIPTION:
Bitter Creek Trib13 0.1
END DESCRIPTION:
XS GIS Cut Line= 3
      1411905.02      6844688.04      1412104.78      6845108.06
      1412655.04      6845037.99
#Sta/Elev= 30
  4534.9 2108.91  4537.6 2108.91  4543.4 2106.84  4549.0 2106.64  4552.3 2105.95
  4566.2 2102.48  4571.7 2102.22  4588.9 2098.39  4611.6 2093.95  4617.1 2093.52
  4623.4 2092.14  4639.8 2091.43  4645.6 2090.71  4656.7 2090.26  4671.2 2088.97
  4676.6 2088.84  4676.9 2088.34  4680.8 2088.34  4681.1 2088.84  4812.8 2088.84
  4848.9 2088.84  5363.1 2088.84  5403.4 2094.21  5432.3 2099.75  5437.3 2100.22
  5443.8 2102.51  5474.0 2107.41  5526.4 2112.01  5534.5 2113.06  5554.7 2113.65
#Mann=8,-1,0
  4534.9   0.035       0  4552.3    0.12       0  4671.2   0.033       0
  4676.6   0.033       0  4681.1   0.033       0  4812.8    0.15       0
  4848.9   0.033       0  5526.4   0.035       0
Bank Sta=4676.6,4681.1
Exp/Cntr=0.3,0.1

Chan Stop Cuts=-1