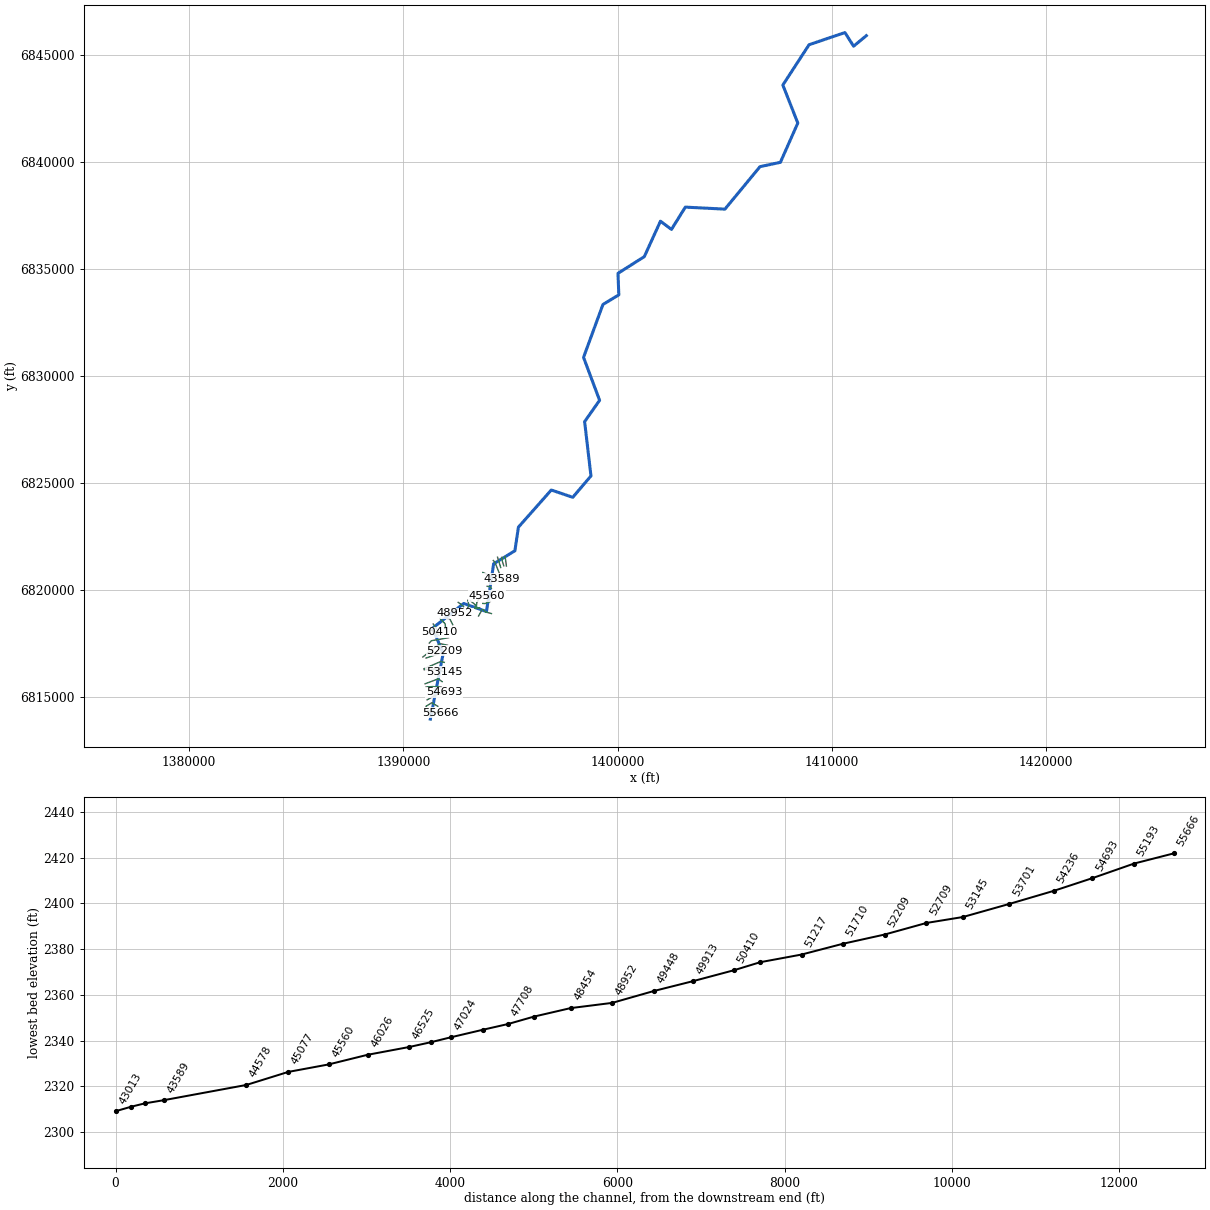
--- Bitter Creek Trib14.prj (project) ---

Proj Title=Bitter Creek Trib14 Base Level Engineering
Current Plan=p01
Default Exp/Contr=0.3,0.1
English Units
Geom File=g01
Flow File=f01
Plan File=p01
Y Axis Title=Elevation
X Axis Title(PF)=Main Channel Distance
X Axis Title(XS)=Station
BEGIN DESCRIPTION:
Bitter Creek Trib14
END DESCRIPTION:
DSS Export Rating Curves= 0
DSS Export Rating Curve Sorted= 0
DSS Export Volume Flow Curves= 0
DXF OffsetX= 0
DXF OffsetY= 0
DXF ScaleX= 1
DXF ScaleY= 10

--- Bitter Creek Trib14.p01 (plan) ---

Plan Title=Multiple Run
Short Identifier=Multiple
Geom File=g01
Flow File=f01
Subcritical Flow
K Sum by GR= 0
Std Step Tol= 0.01
Critical Tol= 0.01
Num of Std Step Trials= 20
Max Error Tol= 0.3
Flow Tol Ratio= 0.001
Split Flow NTrial= 30
Split Flow Tol= 0.02
Split Flow Ratio= 0.02
Log Output Level= 0
Friction Slope Method= 1
Unsteady Friction Slope Method= 2
Unsteady Bridges Friction Slope Method= 1
Parabolic Critical Depth
Global Vel Dist=  1 , 1 , 1
Global Log Level= 0
CheckData=True
Encroach Param= -1, 0, 0, 0
BEGIN DESCRIPTION:
Multiple Run
END DESCRIPTION:

--- Bitter Creek Trib14.f01 (steady flow) ---

Flow Title=Multiple
Number of Profiles=7
Profile Names=10-year,25-year,50-year,1pct_min,100-year,1pct_plu,500-year
River Rch & RM= Bitter Creek Tri,Reach-1,55666
     327     471     594     373     744    1484    1182
River Rch & RM= Bitter Creek Tri,Reach-1,54693
     332     477     601     377     752    1501    1193
River Rch & RM= Bitter Creek Tri,Reach-1,53145
     649     965    1244     796    1587    3167    2621
River Rch & RM= Bitter Creek Tri,Reach-1,46786
     784    1174    1519     976    1947    3885    3241
River Rch & RM= Bitter Creek Tri,Reach-1,43364
     872    1307    1693    1087    2169    4328    3611
River Rch & RM= Bitter Creek Tri,Reach-1,36750
    1223    1861    2434    1577    3147    6280    5334
River Rch & RM= Bitter Creek Tri,Reach-1,30306
    1274    1935    2529    1636    3265    6514    5517
River Rch & RM= Bitter Creek Tri,Reach-1,21977
    1264    1917    2503    1619    3229    6443    5447
River Rch & RM= Bitter Creek Tri,Reach-1,20520
    1390    2114    2765    1790    3572    7126    6041
River Rch & RM= Bitter Creek Tri,Reach-1,16073
    1459    2222    2908    1884    3759    7500    6367
River Rch & RM= Bitter Creek Tri,Reach-1,14318
    1626    2483    3257    2113    4216    8411    7161
River Rch & RM= Bitter Creek Tri,Reach-1,7953
    1680    2565    3364    2182    4353    8686    7390
River Rch & RM= Bitter Creek Tri,Reach-1,3318
    1862    2851    3746    2434    4857    9690    8274
Boundary for River Rch & Prof#=Bitter Creek Tri,Reach-1,1
Up Type=0
Dn Type=3
Dn Slope=0.005
Boundary for River Rch & Prof#=Bitter Creek Tri,Reach-1,2
Up Type=0
Dn Type=3
Dn Slope=0.005
Boundary for River Rch & Prof#=Bitter Creek Tri,Reach-1,3
Up Type=0
Dn Type=3
Dn Slope=0.005
Boundary for River Rch & Prof#=Bitter Creek Tri,Reach-1,4
Up Type=0
Dn Type=3
Dn Slope=0.005
Boundary for River Rch & Prof#=Bitter Creek Tri,Reach-1,5
Up Type=0
Dn Type=3
Dn Slope=0.005
Boundary for River Rch & Prof#=Bitter Creek Tri,Reach-1,6
Up Type=0
Dn Type=3
Dn Slope=0.005
Boundary for River Rch & Prof#=Bitter Creek Tri,Reach-1,7
Up Type=0
Dn Type=3
Dn Slope=0.005

--- Bitter Creek Trib14.g01 (geometry) ---

Geom Title=Existing Conditions
Program Version=4.10

River Reach=Bitter Creek Tri,Reach-1
Reach XY= 30
        1391255.        6813988.      1391855.47      6817058.16
      1391357.91       6818230.1      1392811.08      6819386.43
      1393875.14      6819007.77      1394208.52      6821236.55
      1395201.61      6821846.44      1395365.47      6822947.82
      1396898.87      6824680.26       1397903.5      6824341.47
      1398751.25      6825339.55      1398455.51      6827872.79
      1399154.94      6828867.97      1398405.24      6830872.78
      1399310.47      6833340.44      1400051.46      6833789.46
      1400012.48      6834794.08      1401241.77      6835574.33
      1401994.93      6837226.93      1402508.71      6836845.67
      1403156.59      6837884.33      1405003.61      6837791.02
      1406641.78      6839774.38      1407591.89      6839974.76
      1408405.58      6841808.43      1407707.05      6843582.14
      1408931.48      6845465.01      1410605.25      6846031.02
      1411008.58       6845395.5        1411605.        6845888.

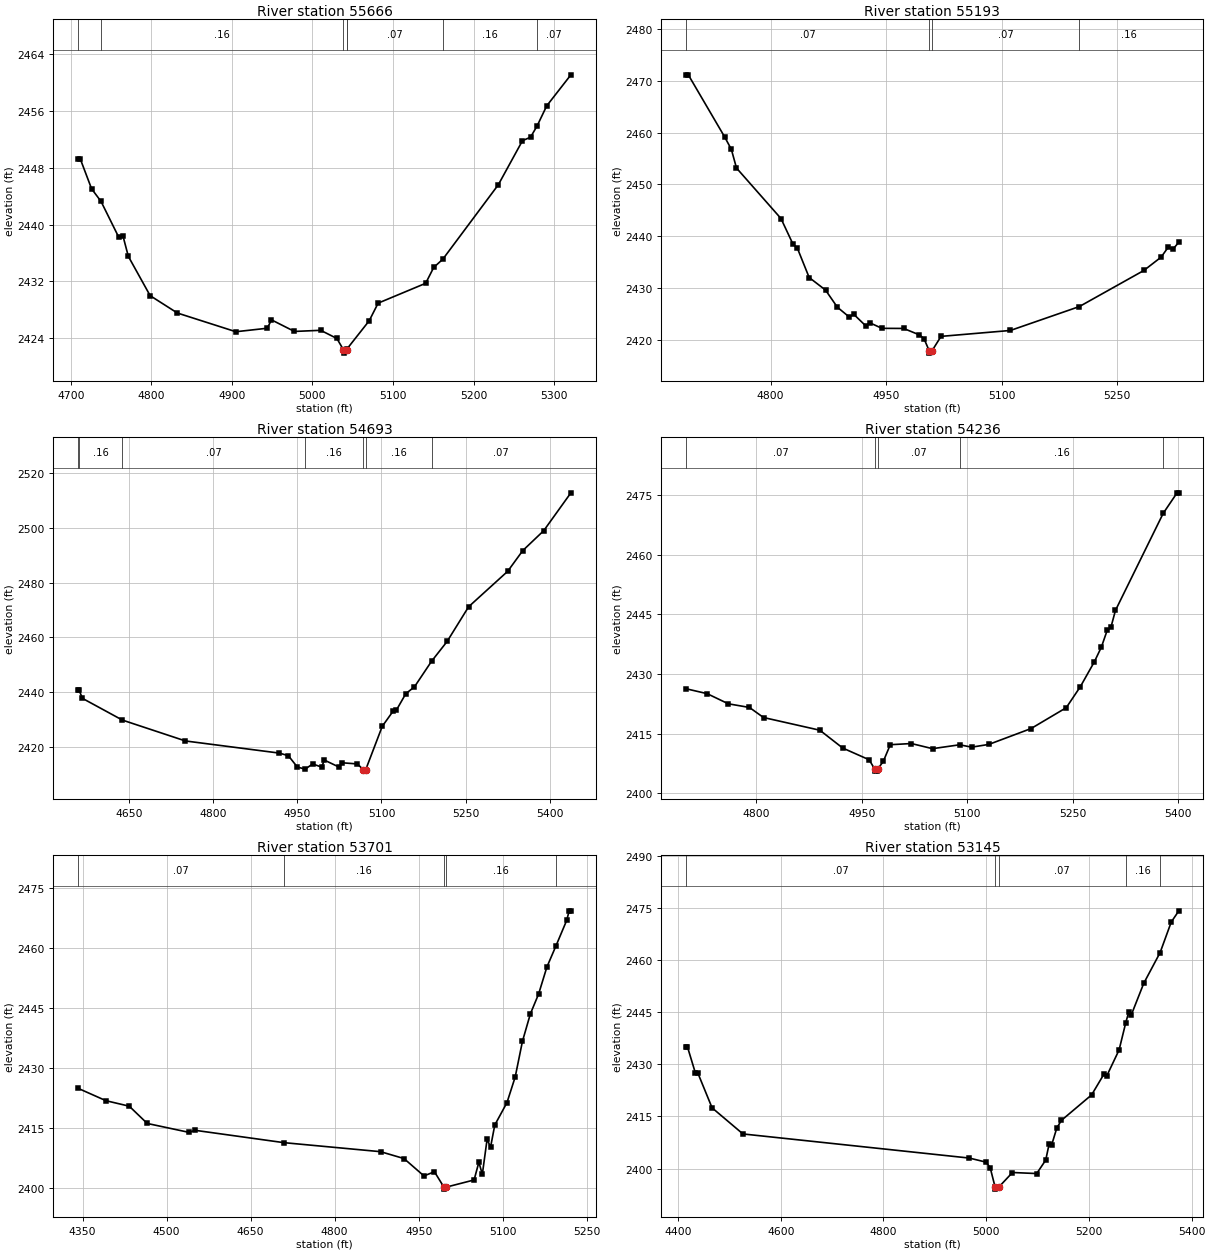
Type RM Length L Ch R = 1 ,55666   ,473,473,473
BEGIN DESCRIPTION:
Bitter Creek Trib14 97.0
END DESCRIPTION:
XS GIS Cut Line= 3
      1391105.05      6814387.99      1391384.67      6814307.79
      1391704.96        6814288.
#Sta/Elev= 30
  4709.1 2449.28  4711.7 2449.28  4725.9 2445.03  4737.6 2443.26  4759.7  2438.2
  4764.9 2438.38  4771.5 2435.53  4798.6    2430  4832.4 2427.56    4905 2424.93
    4944 2425.42  4949.2  2426.6  4977.7 2424.97  5010.3 2425.13  5030.4 2423.98
  5038.4 2422.42  5038.7 2421.92  5042.4 2422.42  5042.8 2422.49  5070.5 2426.47
  5081.6 2428.95  5140.6 2431.74  5150.6 2433.97  5161.9 2435.13  5230.8  2445.6
  5260.8  2451.8  5270.8 2452.29  5278.9 2453.86  5290.9  2456.7  5320.9 2461.06
#Mann= 7 ,-1 , 0
  4709.1     .07       0  4737.6     .16       0  5038.4     .07       0
  5042.4     .16       0  5042.8     .07       0  5161.9     .16       0
  5278.9     .07       0
Bank Sta=5038.4,5042.4
XS Rating Curve= 0 ,0
Exp/Cntr=0.3,0.1

Type RM Length L Ch R = 1 ,55193   ,500,500,500
BEGIN DESCRIPTION:
Bitter Creek Trib14 96.0
END DESCRIPTION:
XS GIS Cut Line= 3
      1391054.96      6814587.98      1391318.22      6814751.67
        1391605.        6814588.
#Sta/Elev= 30
    4690 2471.14    4693 2471.14  4740.2 2459.17  4748.9 2456.78  4755.6 2453.17
  4813.4 2443.43  4828.8 2438.55  4834.7 2437.71    4850 2432.06  4871.3 2429.63
  4886.6 2426.34    4902 2424.45  4907.9 2424.97  4923.2 2422.78  4929.1 2423.31
  4944.5 2422.26  4972.7 2422.24 4993.01 2421.01 4999.07  2420.3  5005.8 2417.98
  5006.1 2417.48  5009.8 2417.98  5021.3 2420.71  5111.4 2421.85    5201 2426.46
  5284.8 2433.42  5307.2 2435.99  5316.5 2437.92  5322.3 2437.48  5330.2 2438.86
#Mann= 4 ,-1 , 0
    4690     .07       0  5005.8     .07       0  5009.8     .07       0
    5201     .16       0
Bank Sta=5005.8,5009.8
XS Rating Curve= 0 ,0
Exp/Cntr=0.3,0.1

Type RM Length L Ch R = 1 ,54693   ,457,457,457
BEGIN DESCRIPTION:
Bitter Creek Trib14 95.0
END DESCRIPTION:
XS GIS Cut Line= 3
      1391105.03      6814888.02      1391488.43      6815104.71
      1391905.03      6815238.01
#Sta/Elev= 30
  4559.6 2440.73  4561.2 2440.73  4567.5 2437.68  4638.5 2429.75  4750.9 2422.11
  4918.3 2417.67  4934.2 2416.71  4950.1 2412.59    4964  2411.8  4977.5 2413.71
  4993.4 2412.55  4998.3 2415.12  5024.9 2412.51  5030.2 2414.13  5057.1 2413.71
  5067.9 2411.58  5068.1 2411.08  5071.9 2411.58  5101.4 2427.46  5121.4 2433.21
  5126.6  2433.4  5143.4 2439.41  5158.8 2441.91  5189.2 2451.25  5216.9 2458.49
  5255.3  2471.2  5324.8 2484.15  5351.7 2491.73  5389.1 2499.03  5437.4 2512.85
#Mann= 7 ,-1 , 0
  4559.6     .07       0  4561.2     .16       0  4638.5     .07       0
    4964     .16       0  5067.9     .07       0  5071.9     .16       0
  5189.2     .07       0
Bank Sta=5067.9,5071.9
XS Rating Curve= 0 ,0
Exp/Cntr=0.3,0.1

Type RM Length L Ch R = 1 ,54236   ,535,535,535
BEGIN DESCRIPTION:
Bitter Creek Trib14 94.0
END DESCRIPTION:
XS GIS Cut Line= 3
      1391054.96        6815488.      1391354.46      6815508.44
      1391755.04        6815488.
#Sta/Elev= 30
  4699.8  2426.3  4729.9 2425.06    4760 2422.51  4790.1 2421.59  4810.1 2419.06
  4890.3 2415.86  4922.8 2411.38  4960.4 2408.43  4968.4 2406.07  4968.7 2405.57
  4972.3 2405.57  4972.5 2406.07  4980.5    2408  4990.5 2412.22  5020.6 2412.51
  5050.6 2411.22  5089.2  2412.2  5106.2  2411.6  5130.7 2412.29  5190.8 2416.28
  5240.9 2421.53  5260.9  2426.8  5280.9 2433.08  5290.9 2436.78  5299.4 2441.12
  5304.4 2441.71  5310.9    2446  5378.9 2470.44  5398.6 2475.59  5401.1 2475.59
#Mann= 5 ,-1 , 0
  4699.8     .07       0  4968.4     .07       0  4972.5     .07       0
  5089.2     .16       0  5378.9     .07       0
Bank Sta=4968.4,4972.5
XS Rating Curve= 0 ,0
Exp/Cntr=0.3,0.1

Type RM Length L Ch R = 1 ,53701   ,556,556,556
BEGIN DESCRIPTION:
Bitter Creek Trib14 93.0
END DESCRIPTION:
XS GIS Cut Line= 3
       1391009.4      6815636.91      1391625.42      6815868.17
      1391805.01        6815738.
#Sta/Elev= 30
    4342 2424.99  4391.9 2421.89  4433.4 2420.52  4465.5 2416.21  4540.2 2413.98
  4550.9  2414.5  4709.2 2411.42  4882.1 2409.16  4923.9 2407.44  4959.5 2403.11
  4978.2 2404.15  4995.1 2400.31  4995.3 2399.81  4999.2 2400.31    5049  2402.1
  5057.5 2406.53  5063.7 2403.52  5072.2 2412.25  5078.4 2410.31  5085.9 2415.81
  5107.7 2421.42  5122.4 2427.84  5135.3 2436.72  5149.5  2443.6  5164.2 2448.55
  5178.9 2455.26  5194.9 2460.48  5214.4 2466.96  5218.7 2469.31  5221.8 2469.31
#Mann= 5 ,-1 , 0
    4342     .07       0  4709.2     .16       0  4995.1     .07       0
  4999.2     .16       0  5194.9     .07       0
Bank Sta=4995.1,4999.2
XS Rating Curve= 0 ,0
Exp/Cntr=0.3,0.1

Type RM Length L Ch R = 1 ,53145   ,436,436,436
BEGIN DESCRIPTION:
Bitter Creek Trib14 92.0
END DESCRIPTION:
XS GIS Cut Line= 3
      1390974.29      6816291.66      1391557.66      6816329.55
      1391905.03      6816187.99
#Sta/Elev= 30
  4415.4 2434.97  4418.3 2434.97  4433.6 2427.51  4438.7 2427.38  4466.2 2417.45
  4526.3 2409.94  4967.3    2403    5000 2401.82  5007.9 2400.15  5017.5 2394.57
    5018 2394.07    5024 2394.57  5051.1 2398.85  5098.3 2398.55  5115.9 2402.42
  5122.3 2406.91  5127.7  2406.9  5137.5 2411.66  5146.4 2413.84  5205.3 2421.18
  5229.3 2427.15  5234.7 2426.61  5258.8 2434.12  5271.7  2441.9  5277.4  2444.9
  5282.8 2444.28  5306.9  2453.3  5338.7 2462.12  5360.3 2470.88  5375.1 2474.11
#Mann= 5 ,-1 , 0
  4415.4     .07       0  5017.5     .07       0    5024     .07       0
  5271.7     .16       0  5338.7     .07       0
Bank Sta=5017.5,5024
XS Rating Curve= 0 ,0
Exp/Cntr=0.3,0.1

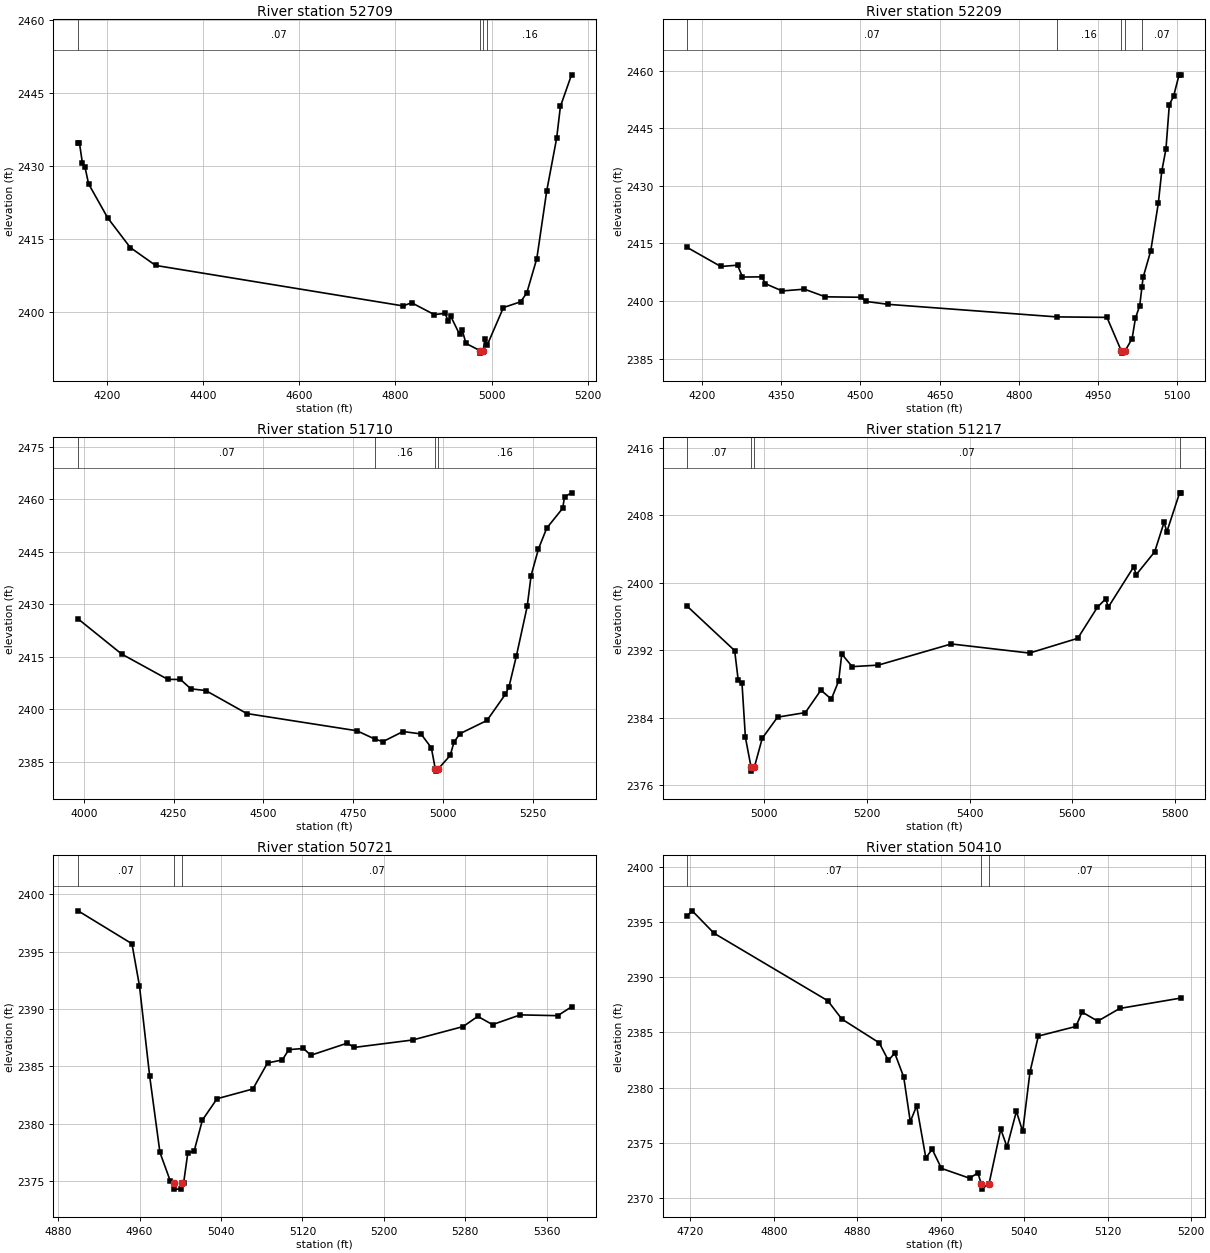
Type RM Length L Ch R = 1 ,52709   ,500,500,500
BEGIN DESCRIPTION:
Bitter Creek Trib14 91.0
END DESCRIPTION:
XS GIS Cut Line= 3
      1390955.02      6816338.01      1391744.16      6816678.35
      1391904.98      6816638.01
#Sta/Elev= 30
  4140.6 2434.73  4143.3 2434.73  4149.6  2430.5  4155.1 2429.62  4162.4 2426.25
  4202.1 2419.26  4249.1 2413.16  4301.6 2409.49  4815.8 2401.17  4833.6 2401.82
  4880.6 2399.39  4902.9 2399.64  4909.5 2398.11    4915 2399.01  4933.1 2395.35
  4938.5 2396.26  4946.5 2393.46  4975.9 2391.97  4976.4 2391.47  4982.4 2391.97
  4985.5 2394.34  4990.7 2393.14  5024.3 2400.83  5060.3 2402.03    5073 2403.88
  5093.7 2410.91  5114.3 2424.82  5134.9 2435.62  5142.7 2442.15  5165.8 2448.65
#Mann= 4 ,-1 , 0
  4140.6     .07       0  4975.9     .07       0  4982.4     .07       0
  4990.7     .16       0
Bank Sta=4975.9,4982.4
XS Rating Curve= 0 ,0
Exp/Cntr=0.3,0.1

Type RM Length L Ch R = 1 ,52209   ,499,499,499
BEGIN DESCRIPTION:
Bitter Creek Trib14 90.0
END DESCRIPTION:
XS GIS Cut Line= 3
      1391055.01      6816838.01      1391838.79      6817104.67
      1391904.98      6817187.98
#Sta/Elev= 30
  4172.1 2413.92  4235.5 2408.97  4267.2 2409.31  4276.6 2406.22  4313.2 2406.27
    4320 2404.48  4351.7  2402.6  4393.9 2403.06  4433.4 2401.07  4501.4 2400.95
  4510.1 2399.87  4552.4 2399.11  4871.5 2395.84  4966.7 2395.71  4994.1  2386.9
  4994.6  2386.4  5000.7  2386.9  5014.3 2390.18  5020.7 2395.55  5028.7 2398.75
    5033  2403.7  5035.1 2406.11  5049.6 2413.05    5064 2425.51  5070.4 2433.74
  5078.4 2439.57  5084.8 2451.14  5092.8 2453.29  5103.2  2458.9  5106.4  2458.9
#Mann= 5 ,-1 , 0
  4172.1     .07       0  4871.5     .16       0  4994.1     .07       0
  5000.7     .16       0    5033     .07       0
Bank Sta=4994.1,5000.7
XS Rating Curve= 0 ,0
Exp/Cntr=0.3,0.1

Type RM Length L Ch R = 1 ,51710   ,493,493,493
BEGIN DESCRIPTION:
Bitter Creek Trib14 89.0
END DESCRIPTION:
XS GIS Cut Line= 3
      1390905.01        6816888.      1391705.36      6817513.21
      1392054.96      6817438.01
#Sta/Elev= 30
  3984.4 2425.82  4105.6 2415.79    4234 2408.56  4269.3 2408.52  4298.2 2405.86
  4339.8 2405.36  4453.9  2398.8  4760.4 2393.88  4810.9 2391.48  4832.7 2390.78
  4888.8 2393.67  4938.6 2392.98  4967.5 2389.02  4978.7 2382.86  4979.2 2382.36
  4985.3 2382.86  5020.1 2386.84  5030.3  2390.6  5047.1 2393.05  5122.4 2396.83
  5173.5  2404.3  5183.7  2406.5  5204.2 2415.25  5234.3 2429.42  5245.1 2438.19
  5265.6  2445.8  5288.7 2451.75    5333 2457.39  5338.1 2460.64  5357.6 2461.81
#Mann= 4 ,-1 , 0
  3984.4     .07       0  4810.9     .16       0  4978.7     .07       0
  4985.3     .16       0
Bank Sta=4978.7,4985.3
XS Rating Curve= 0 ,0
Exp/Cntr=0.3,0.1

Type RM Length L Ch R = 1 ,51217   ,496,496,496
BEGIN DESCRIPTION:
Bitter Creek Trib14 88.0
END DESCRIPTION:
XS GIS Cut Line= 3
        1391205.        6817538.      1391305.93      6817648.15
      1392104.99        6817788.
#Sta/Elev= 30
  4850.6 2397.19  4942.8 2391.94  4949.6 2388.48    4957 2388.12  4963.7 2381.66
  4974.6 2378.15  4975.1 2377.65  4981.3 2378.15  4996.5 2381.55  5026.3 2384.05
  5080.3 2384.59  5110.7 2387.25    5131 2386.19  5145.2 2388.33  5151.3 2391.53
  5171.6 2390.04  5222.4 2390.22  5364.5 2392.73  5516.8 2391.65  5610.7  2393.4
  5648.8 2397.07  5665.1 2398.08  5670.2  2397.1  5719.5 2401.86  5724.6 2400.95
  5760.5 2403.66  5778.9 2407.19    5784    2406    5809 2410.65  5811.2 2410.65
#Mann= 4 ,-1 , 0
  4850.6     .07       0  4974.6     .07       0  4981.3     .07       0
    5809     .16       0
Bank Sta=4974.6,4981.3
XS Rating Curve= 0 ,0
Exp/Cntr=0.3,0.1

Type RM Length L Ch R = 1 ,50721   ,311,311,311
BEGIN DESCRIPTION:
Bitter Creek Trib14 87.0
END DESCRIPTION:
XS GIS Cut Line= 3
      1391255.02        6818138.      1391354.93      6818128.07
      1391655.01      6817887.99
#Sta/Elev= 30
  4899.6 2398.55  4952.5 2395.68  4959.9    2392  4969.9 2384.15    4980 2377.49
    4990 2375.04  4993.7 2374.79  4994.2 2374.29  5000.8 2374.29  5001.3 2374.79
  5003.2 2374.79  5007.3  2377.4  5013.7 2377.64  5021.7 2380.31  5036.1 2382.17
  5071.3 2383.02  5085.7 2385.29  5100.2 2385.55  5106.6 2386.45    5121 2386.55
  5128.2 2385.96  5164.2 2387.02  5170.6 2386.64  5228.2 2387.29  5277.8 2388.46
  5292.2 2389.35  5306.7 2388.63  5333.9 2389.48  5370.7 2389.41  5384.3 2390.18
#Mann= 3 ,-1 , 0
  4899.6     .07       0  4993.7     .07       0  5001.3     .07       0
Bank Sta=4993.7,5001.3
XS Rating Curve= 0 ,0
Exp/Cntr=0.3,0.1

Type RM Length L Ch R = 1 ,50410   ,497,497,497
BEGIN DESCRIPTION:
Bitter Creek Trib14 86.0
END DESCRIPTION:
XS GIS Cut Line= 3
      1391388.76      6818428.87      1391549.09      6818195.79
      1391654.98      6818038.03
#Sta/Elev= 30
  4717.1 2395.56  4721.8    2396  4742.7 2393.97  4851.7 2387.86  4865.2  2386.2
    4901 2384.05  4909.8 2382.45  4915.9 2383.12  4924.5 2380.95  4930.8 2376.91
  4936.9 2378.34  4945.7 2373.63  4951.8 2374.41  4960.6 2372.68  4987.6 2371.79
  4995.6 2372.27  4998.7  2371.3  4999.2  2370.8  5006.3  2371.3  5017.5 2376.23
  5023.5 2374.62  5032.5 2377.85  5038.5 2376.02  5045.5  2381.4  5053.5 2384.66
  5089.5 2385.53  5095.5 2386.83  5110.5 2386.01  5131.5 2387.16    5190  2388.1
#Mann= 3 ,-1 , 0
  4717.1     .07       0  4998.7     .07       0  5006.3     .07       0
Bank Sta=4998.7,5006.3
XS Rating Curve= 0 ,0
Exp/Cntr=0.3,0.1

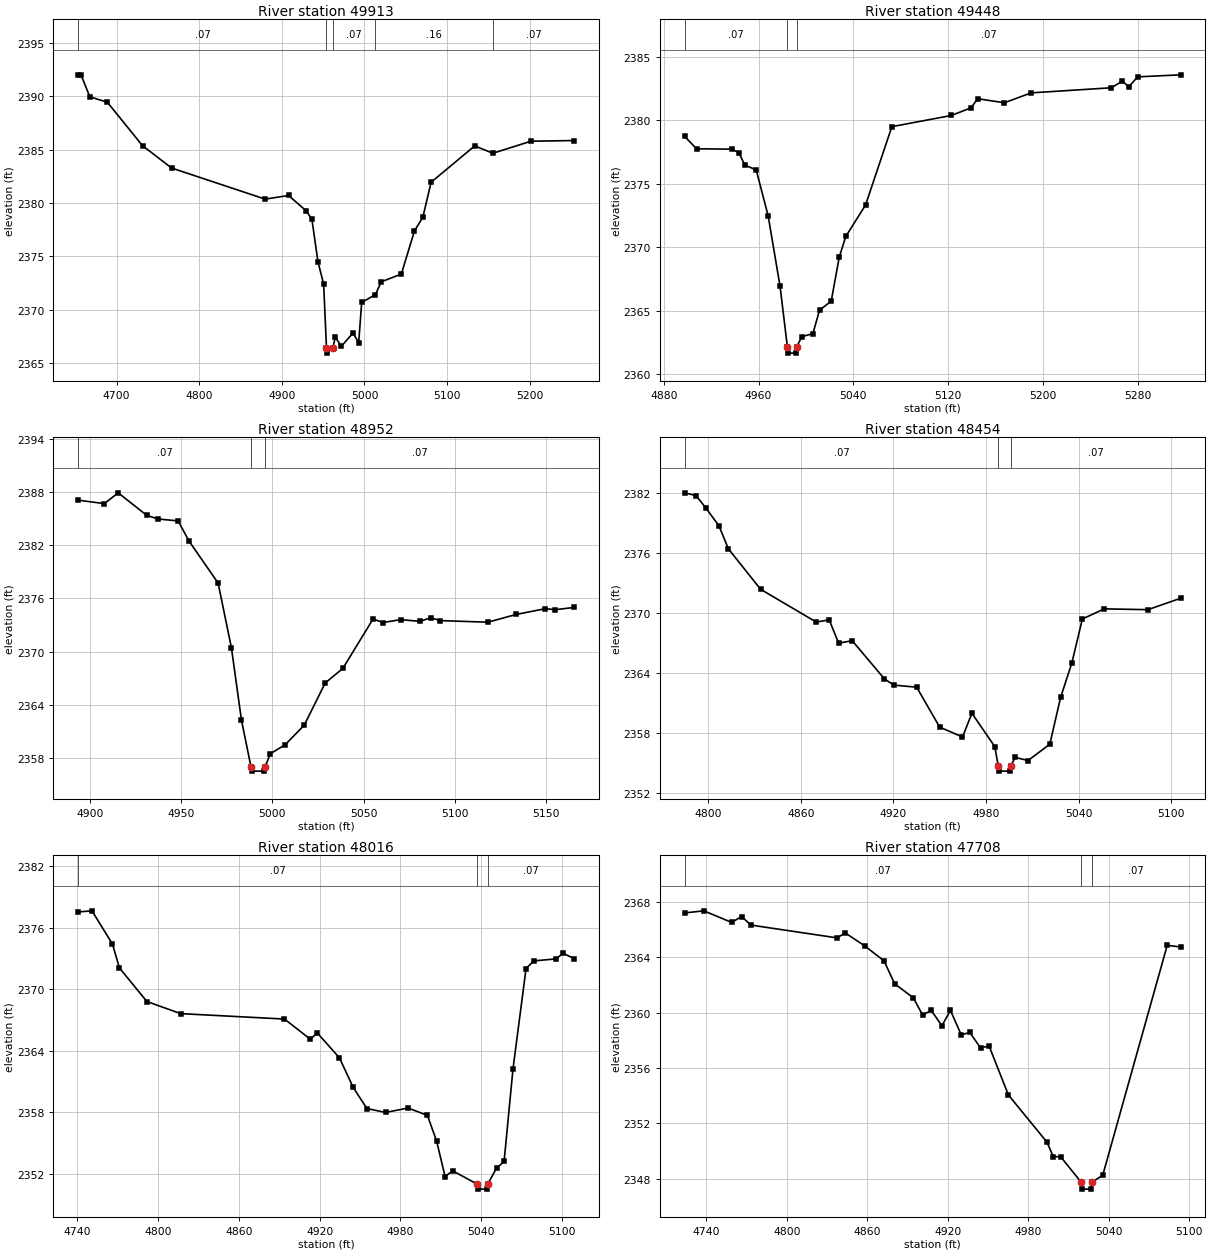
Type RM Length L Ch R = 1 ,49913   ,465,465,465
BEGIN DESCRIPTION:
Bitter Creek Trib14 85.0
END DESCRIPTION:
XS GIS Cut Line= 3
      1391705.03      6818687.97      1391944.95      6818438.11
      1391974.13       6818186.1
#Sta/Elev= 30
  4653.6 2391.99    4657 2391.99  4667.6 2389.94  4688.9 2389.42  4731.4 2385.36
  4766.6 2383.27  4879.8 2380.36  4908.1  2380.7  4929.5 2379.26  4936.4 2378.46
  4943.7  2374.5  4950.6  2372.4    4954 2366.45  4954.5 2365.95  4961.7 2366.45
  4964.7 2367.44    4972 2366.59  4986.1 2367.83    4993 2366.93  4996.6 2370.69
  5013.3 2371.43  5020.2 2372.62  5044.6 2373.35  5060.5 2377.39  5070.6 2378.66
  5080.6 2381.94  5133.4 2385.34  5155.3 2384.65  5201.5 2385.78  5253.7 2385.84
#Mann= 5 ,-1 , 0
  4653.6     .07       0    4954     .07       0  4961.7     .07       0
  5013.3     .16       0  5155.3     .07       0
Bank Sta=4954,4961.7
XS Rating Curve= 0 ,0
Exp/Cntr=0.3,0.1

Type RM Length L Ch R = 1 ,49448   ,496,496,496
BEGIN DESCRIPTION:
Bitter Creek Trib14 84.0
END DESCRIPTION:
XS GIS Cut Line= 3
      1392055.04        6818688.      1392156.74      6818676.95
      1392300.58       6818395.7
#Sta/Elev= 30
  4897.7 2378.72  4907.7 2377.75  4937.9 2377.72  4943.5 2377.41  4948.5 2376.46
    4958 2376.09  4968.1 2372.47  4978.1 2366.94  4984.3 2362.17  4984.8 2361.67
  4991.6 2361.67  4992.1 2362.17  4996.6 2362.97  5005.8  2363.2  5011.4 2365.04
  5021.3 2365.77    5028 2369.21  5033.6 2370.86  5050.2 2373.32  5072.4 2379.49
  5122.5 2380.37  5139.1 2380.97  5144.8 2381.69  5167.3 2381.37  5189.8 2382.15
  5257.2 2382.55  5266.7 2383.06  5272.4 2382.64  5279.6 2383.41  5315.9 2383.57
#Mann= 3 ,-1 , 0
  4897.7     .07       0  4984.3     .07       0  4992.1     .07       0
Bank Sta=4984.3,4992.1
XS Rating Curve= 0 ,0
Exp/Cntr=0.3,0.1

Type RM Length L Ch R = 1 ,48952   ,498,498,498
BEGIN DESCRIPTION:
Bitter Creek Trib14 83.0
END DESCRIPTION:
XS GIS Cut Line= 3
      1392255.04      6819137.98      1392352.09       6819094.6
        1392405.        6818938.
#Sta/Elev= 30
  4893.7 2387.11    4908 2386.72  4915.6 2387.94  4931.2  2385.4  4937.5 2384.98
  4948.4 2384.77  4954.4 2382.48  4970.3 2377.75  4977.6 2370.43  4983.1 2362.26
  4988.3 2356.99  4988.8 2356.49  4995.6 2356.49  4996.1 2356.99  4998.9 2358.46
    5007 2359.46  5017.5 2361.69    5029 2366.46  5038.6 2368.09  5055.2 2373.69
  5060.5 2373.28  5070.3 2373.61  5080.9 2373.41  5086.7 2373.83  5091.9  2373.5
  5118.1 2373.32  5133.6  2374.2  5149.6 2374.85  5154.9 2374.73  5165.3 2374.99
#Mann= 3 ,-1 , 0
  4893.7     .07       0  4988.3     .07       0  4996.1     .07       0
Bank Sta=4988.3,4996.1
XS Rating Curve= 0 ,0
Exp/Cntr=0.3,0.1

Type RM Length L Ch R = 1 ,48454   ,438,438,438
BEGIN DESCRIPTION:
Bitter Creek Trib14 82.0
END DESCRIPTION:
XS GIS Cut Line= 3
      1392555.04      6819437.97      1392731.59      6819314.76
        1392805.      6819238.01
#Sta/Elev= 30
  4784.7 2382.02  4792.1 2381.74  4798.2 2380.55  4806.9 2378.73    4813 2376.43
  4833.9 2372.38    4870  2369.1  4878.4 2369.32  4884.5 2366.99  4893.3 2367.24
  4914.2 2363.42  4920.3  2362.8  4935.1 2362.59    4950  2358.6  4964.8 2357.61
  4970.9 2359.98  4985.7 2356.66    4988  2354.7  4988.5  2354.2  4995.5  2354.2
    4996  2354.7    4999 2355.57  5007.3 2355.26  5021.4 2356.89  5028.4 2361.57
  5035.6 2364.96  5042.5 2369.41  5056.7 2370.42    5085 2370.34  5106.2 2371.48
#Mann= 3 ,-1 , 0
  4784.7     .07       0    4988     .07       0    4996     .07       0
Bank Sta=4988,4996
XS Rating Curve= 0 ,0
Exp/Cntr=0.3,0.1

Type RM Length L Ch R = 1 ,48016   ,308,308,308
BEGIN DESCRIPTION:
Bitter Creek Trib14 81.0
END DESCRIPTION:
XS GIS Cut Line= 3
        1393005.      6819538.02      1393056.47      6819283.98
      1393005.01      6819188.01
#Sta/Elev= 30
  4740.8 2377.55    4751 2377.66  4766.2 2374.42  4771.4 2372.08  4791.8  2368.8
  4816.9 2367.62  4893.9 2367.09  4913.1 2365.12  4918.2 2365.74  4934.7  2363.3
  4944.9 2360.41  4955.1 2358.35  4968.9 2357.97  4985.7  2358.4    5000 2357.68
  5006.8 2355.18  5013.1 2351.71  5018.7 2352.27  5036.8 2350.98  5037.3 2350.48
  5044.3 2350.48  5044.8 2350.98  5051.3 2352.53  5056.9 2353.18  5063.5 2362.22
  5073.2 2372.02  5078.9 2372.77  5095.1 2372.96  5100.8  2373.5  5108.9    2373
#Mann= 3 ,-1 , 0
  4740.8     .07       0  5036.8     .07       0  5044.8     .07       0
Bank Sta=5036.8,5044.8
XS Rating Curve= 0 ,0
Exp/Cntr=0.3,0.1

Type RM Length L Ch R = 1 ,47708   ,302,302,302
BEGIN DESCRIPTION:
Bitter Creek Trib14 80.0
END DESCRIPTION:
XS GIS Cut Line= 3
      1393131.94      6819504.39      1393347.32      6819331.48
        1393355.      6819237.99
#Sta/Elev= 30
  4723.8 2367.19  4738.1 2367.34  4758.9  2366.5  4766.2 2366.93  4773.3 2366.31
  4837.3 2365.39  4843.7 2365.74  4858.1 2364.81  4872.5 2363.73  4880.5 2362.07
  4894.4 2361.06  4901.3 2359.82  4907.7 2360.15  4915.7 2359.05  4922.1 2360.15
  4930.1 2358.39  4936.5 2358.56  4944.5 2357.45  4950.9 2357.58  4965.3 2354.05
  4994.1 2350.64  4998.8 2349.59  5004.3 2349.59  5019.6 2347.75  5020.1 2347.25
  5027.1 2347.25  5027.6 2347.75  5035.7 2348.25  5083.8 2364.85  5093.8 2364.73
#Mann= 3 ,-1 , 0
  4723.8     .07       0  5019.6     .07       0  5027.6     .07       0
Bank Sta=5019.6,5027.6
XS Rating Curve= 0 ,0
Exp/Cntr=0.3,0.1

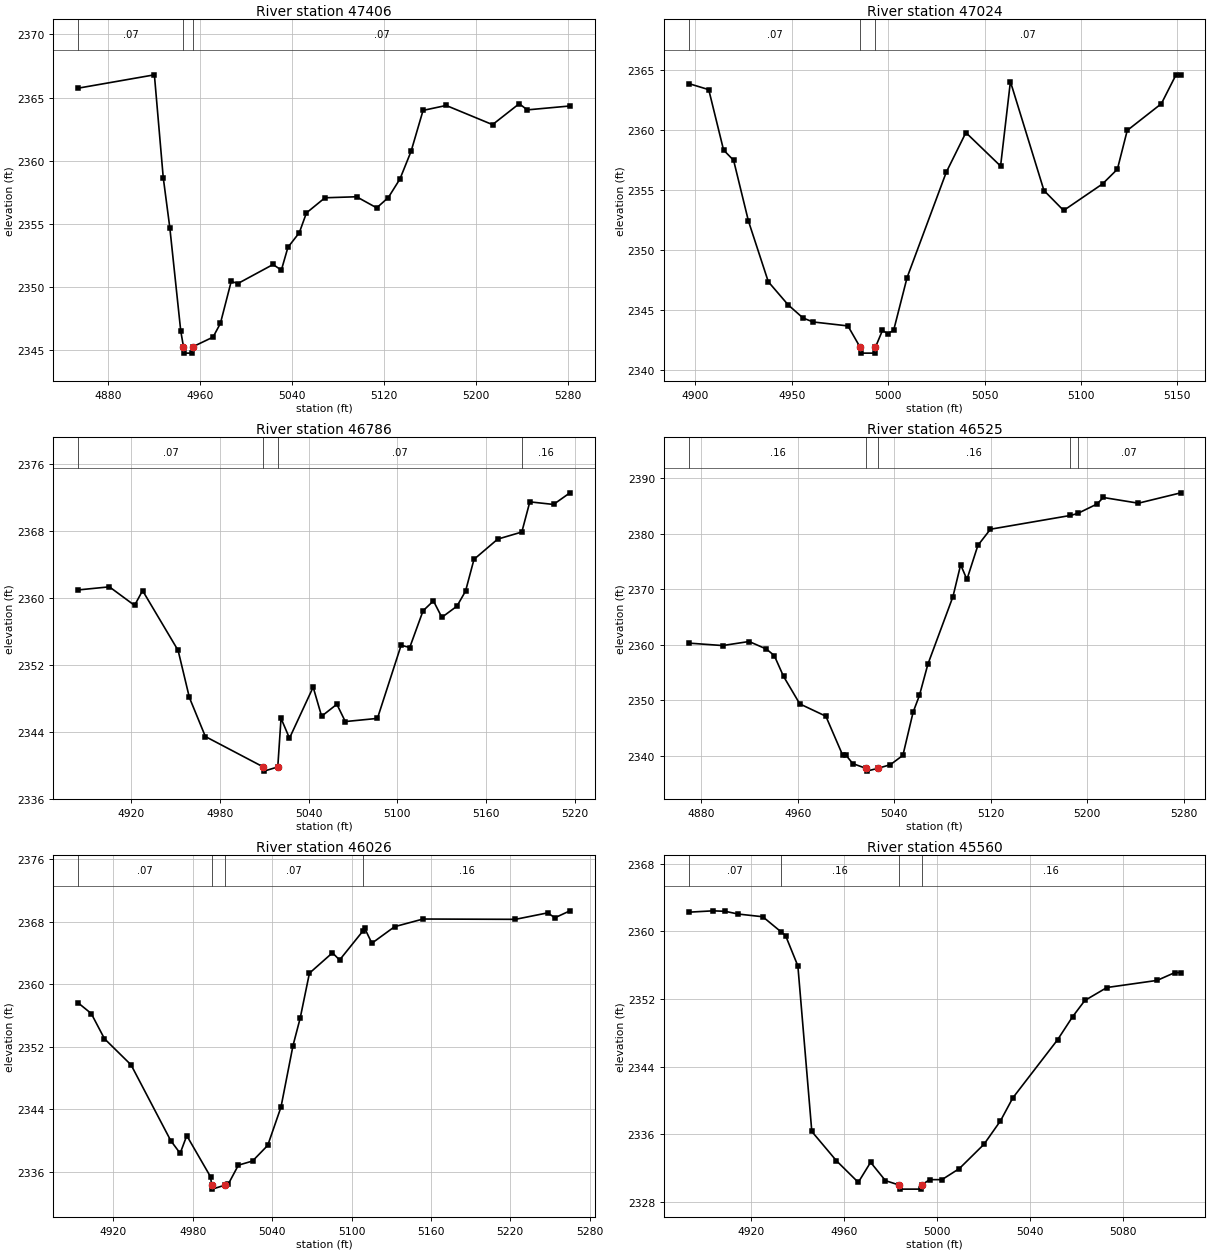
Type RM Length L Ch R = 1 ,47406   ,382,382,382
BEGIN DESCRIPTION:
Bitter Creek Trib14 79.1
END DESCRIPTION:
XS GIS Cut Line= 4
      1393547.47      6819645.75      1393475.58      6819518.79
      1393424.93      6819426.49      1393404.74      6819251.13
#Sta/Elev= 30
  4854.1 2365.74  4920.5  2366.8  4928.2 2358.65  4933.9 2354.69  4943.4  2346.5
  4945.8 2345.23  4946.3 2344.73  4953.3 2344.73  4953.8 2345.23  4971.5    2346
  4977.9 2347.09  4987.3 2350.42  4993.1 2350.25  5023.7 2351.76  5030.9 2351.31
  5036.6 2353.12  5046.5 2354.28  5052.7 2355.85  5068.8 2357.05  5096.3 2357.13
  5113.8 2356.25  5123.9 2357.07    5134 2358.54  5143.7 2360.74  5154.1 2363.98
  5174.2 2364.37  5214.5 2362.85  5237.7 2364.51  5244.7 2364.02  5281.8 2364.33
#Mann= 3 ,-1 , 0
  4854.1     .07       0  4945.8     .07       0  4953.8     .07       0
Bank Sta=4945.8,4953.8
XS Rating Curve= 0 ,0
Exp/Cntr=0.3,0.1

Type RM Length L Ch R = 1 ,47024   ,238,238,238
BEGIN DESCRIPTION:
Bitter Creek Trib14 79.0
END DESCRIPTION:
XS GIS Cut Line= 3
        1393555.        6819188.       1393454.7      6819162.88
        1393305.        6819188.
#Sta/Elev= 30
  4896.6 2363.83  4906.9 2363.33  4914.6 2358.31  4919.8 2357.46  4927.5 2352.41
  4937.8 2347.37  4948.1 2345.45  4955.8 2344.36    4961 2344.03  4979.1  2343.7
  4985.4 2341.94  4985.9 2341.44  4992.9 2341.44  4993.4 2341.94    4997 2343.32
  4999.7 2343.07  5002.8 2343.32  5009.8 2347.72  5030.1 2356.46  5040.3 2359.76
  5058.3 2356.98  5063.4    2364  5080.8 2354.95    5091 2353.29  5111.2  2355.5
  5118.9 2356.72    5124 2359.94  5141.7 2362.16  5149.3 2364.56  5151.8 2364.56
#Mann= 3 ,-1 , 0
  4896.6     .07       0  4985.4     .07       0  4993.4     .07       0
Bank Sta=4985.4,4993.4
XS Rating Curve= 0 ,0
Exp/Cntr=0.3,0.1

Type RM Length L Ch R = 1 ,46786   ,261,261,261
BEGIN DESCRIPTION:
Bitter Creek Trib14 78.1
END DESCRIPTION:
XS GIS Cut Line= 3
       1393654.7      6819097.64      1393611.03      6818990.49
      1393505.74      6818801.32
#Sta/Elev= 30
  4884.3 2360.97  4905.5 2361.34  4922.5 2359.12  4927.9 2360.89  4951.9 2353.73
  4959.5  2348.1  4970.3 2343.43  5009.4 2339.79  5009.9 2339.29  5019.2 2339.79
  5021.4 2345.61  5027.1 2343.23  5043.1 2349.34  5048.8 2345.86  5059.1 2347.29
  5064.8 2345.22  5086.5  2345.6  5102.5 2354.36  5108.3 2354.08  5117.3 2358.47
  5124.3 2359.66    5130 2357.69  5140.2 2359.03    5146 2360.83  5151.7 2364.63
  5167.7 2367.05    5184  2367.9  5189.4 2371.51  5205.4  2371.2  5216.5 2372.59
#Mann= 4 ,-1 , 0
  4884.3     .07       0  5009.4     .07       0  5019.2     .07       0
    5184     .16       0
Bank Sta=5009.4,5019.2
XS Rating Curve= 0 ,0
Exp/Cntr=0.3,0.1

Type RM Length L Ch R = 1 ,46525   ,499,499,499
BEGIN DESCRIPTION:
Bitter Creek Trib14 78.0
END DESCRIPTION:
XS GIS Cut Line= 3
      1393755.01      6819087.99      1393839.67       6818988.8
      1394107.12      6818914.44
#Sta/Elev= 30
  4869.6 2360.28  4897.6 2359.84  4919.5 2360.57  4933.8 2359.22  4940.4 2358.04
  4948.1 2354.28  4961.6 2349.31  4983.2 2347.09  4997.2 2340.03    5000 2340.03
  5005.5 2338.54  5016.5 2337.68    5017 2337.18  5026.3 2337.68  5036.7 2338.34
  5047.1 2340.03  5055.6 2347.84  5060.8 2350.83  5067.8 2356.46  5088.6 2368.66
    5095 2374.42  5100.2 2371.77  5109.3 2377.92  5119.7 2380.83  5186.1 2383.32
    5192 2383.67  5208.1 2385.38  5213.3 2386.56  5242.4 2385.53  5277.6  2387.4
#Mann= 5 ,-1 , 0
  4869.6     .16       0  5016.5     .07       0  5026.3     .16       0
  5186.1     .16       0    5192     .07       0
Bank Sta=5016.5,5026.3
XS Rating Curve= 0 ,0
Exp/Cntr=0.3,0.1

Type RM Length L Ch R = 1 ,46026   ,466,466,466
BEGIN DESCRIPTION:
Bitter Creek Trib14 77.0
END DESCRIPTION:
XS GIS Cut Line= 3
      1393705.02        6819388.      1393811.51      6819381.27
      1394058.31      6819478.06
#Sta/Elev= 30
  4893.3 2357.64  4903.3 2356.26  4913.3 2353.03  4933.4 2349.68  4963.4 2339.97
  4970.5 2338.35  4975.5 2340.61  4993.5 2335.33  4994.3 2334.26  4994.8 2333.76
  5004.1 2334.26  5006.9 2334.41  5014.5 2336.83  5025.2 2337.36  5036.7 2339.37
  5046.7 2344.27  5055.8 2352.16  5061.2 2355.66  5068.2 2361.43  5085.6 2364.04
    5091 2363.12  5108.9 2366.89    5110 2367.17  5115.4 2365.27  5132.6 2367.39
  5154.1 2368.37  5223.9 2368.33  5248.3 2369.16  5253.7 2368.53  5265.1 2369.42
#Mann= 4 ,-1 , 0
  4893.3     .07       0  4994.3     .07       0  5004.1     .07       0
  5108.9     .16       0
Bank Sta=4994.3,5004.1
XS Rating Curve= 0 ,0
Exp/Cntr=0.3,0.1

Type RM Length L Ch R = 1 ,45560   ,483,483,483
BEGIN DESCRIPTION:
Bitter Creek Trib14 76.0
END DESCRIPTION:
XS GIS Cut Line= 3
      1393704.95      6819737.98      1393805.87      6819772.64
      1393904.99        6819738.
#Sta/Elev= 30
  4893.3 2362.26  4903.7 2362.42    4909 2362.36  4914.5 2362.04  4925.1 2361.72
    4933 2359.93  4934.9  2359.5  4940.2 2355.91  4946.2 2336.35  4956.8 2332.89
  4966.2 2330.34  4971.5 2332.71  4977.9 2330.54  4983.6 2330.04  4984.1 2329.54
    4993 2329.54  4993.5 2330.04  4996.9 2330.66  5002.2 2330.66  5009.7 2331.97
  5020.3 2334.84  5027.4 2337.61  5032.7 2340.32    5052  2347.2  5058.4  2349.9
  5063.7 2351.83  5073.2 2353.36  5094.8  2354.2  5102.4 2355.12    5105 2355.12
#Mann= 4 ,-1 , 0
  4893.3     .07       0    4933     .16       0  4983.6     .07       0
  4993.5     .16       0
Bank Sta=4983.6,4993.5
XS Rating Curve= 0 ,0
Exp/Cntr=0.3,0.1

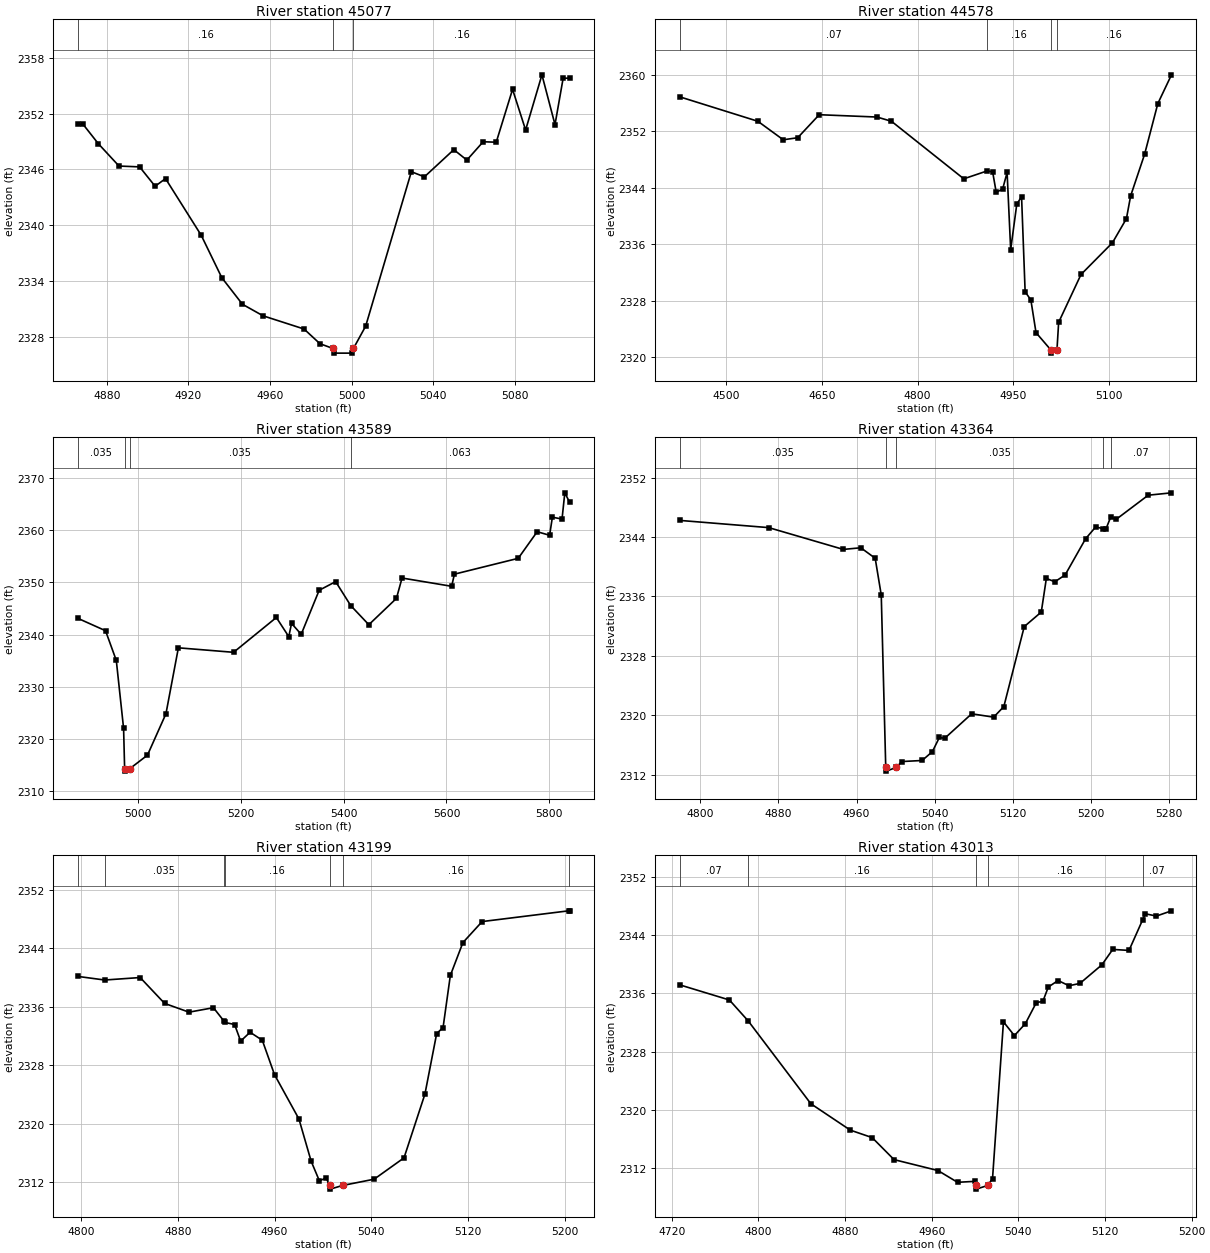
Type RM Length L Ch R = 1 ,45077   ,499,499,499
BEGIN DESCRIPTION:
Bitter Creek Trib14 75.0
END DESCRIPTION:
XS GIS Cut Line= 3
      1393905.04      6820187.99      1394038.12      6820171.42
      1394104.98      6820088.02
#Sta/Elev= 30
  4865.9 2350.84  4868.4 2350.84  4875.9 2348.75    4886 2346.36  4896.1 2346.27
  4903.7 2344.19  4908.8 2345.01  4926.3 2338.92  4936.4 2334.36  4946.5 2331.51
  4956.6 2330.27  4976.7 2328.85  4984.5 2327.27  4990.9 2326.76  4991.4 2326.26
  5000.4 2326.26  5000.9 2326.76  5006.9 2329.16  5029.3 2345.75  5035.7  2345.2
  5050.1 2348.12  5056.5    2347  5064.5 2348.97  5070.9 2348.92  5078.9  2354.6
  5085.3 2350.23  5093.3 2356.16  5099.7 2350.81  5103.7  2355.8  5106.9  2355.8
#Mann= 3 ,-1 , 0
  4865.9     .16       0  4990.9     .07       0  5000.9     .16       0
Bank Sta=4990.9,5000.9
XS Rating Curve= 0 ,0
Exp/Cntr=0.3,0.1

Type RM Length L Ch R = 1 ,44578   ,989,989,989
BEGIN DESCRIPTION:
Bitter Creek Trib14 74.0
END DESCRIPTION:
XS GIS Cut Line= 3
      1393707.58      6820834.92      1394224.99      6820588.02
      1394354.99      6820438.01
#Sta/Elev= 30
  4426.7 2356.87  4549.3 2353.41  4589.1 2350.79  4611.8 2351.08  4645.6 2354.34
  4736.3 2354.01    4759 2353.41  4872.5 2345.26  4909.2 2346.38  4917.8 2346.24
  4923.4 2343.35  4933.5 2343.81  4940.5 2346.16  4946.1 2335.23  4955.7 2341.67
  4963.2 2342.73  4968.8 2329.26  4977.8  2328.1  4985.9 2323.47  5008.7 2321.07
  5009.2 2320.57  5018.8 2321.07  5021.4 2324.93  5056.5 2331.71  5105.9 2336.21
  5127.8 2339.62  5134.4 2342.84  5156.3 2348.73  5177.1 2355.92  5198.5 2359.99
#Mann= 4 ,-1 , 0
  4426.7     .07       0  4909.2     .16       0  5008.7     .07       0
  5018.8     .16       0
Bank Sta=5008.7,5018.8
XS Rating Curve= 0 ,0
Exp/Cntr=0.3,0.1

Type RM Length L Ch R = 1 ,43589   ,225,225,225
BEGIN DESCRIPTION:
Bitter Creek Trib14 72.0
END DESCRIPTION:
XS GIS Cut Line= 3
      1394192.97       6821391.7      1394266.11      6821315.66
      1394583.89      6820525.04
#Sta/Elev= 30
  4882.4 2343.11    4936 2340.75    4957 2335.06  4971.2 2322.06  4973.2 2314.39
  4973.7 2313.89  4983.7 2314.39  5017.7 2316.95  5053.7 2324.87  5077.9 2337.48
  5185.4 2336.62  5268.7 2343.28  5292.9 2339.62  5298.3 2342.15  5317.1 2340.06
  5352.1 2348.49  5384.2 2350.14  5413.5 2345.57  5448.8  2341.9  5502.6 2346.94
  5513.5 2350.83  5610.1 2349.25  5615.5 2351.57  5739.8  2354.6  5776.7 2359.69
  5800.9 2359.01  5806.3 2362.47  5825.1 2362.11  5830.5 2367.13    5840  2365.3
#Mann= 4 ,-1 , 0
  4882.4    .035       0  4973.2    .035       0  4983.7    .035       0
  5413.5    .063       0
Bank Sta=4973.2,4983.7
XS Rating Curve= 0 ,0
Exp/Cntr=0.3,0.1

Type RM Length L Ch R = 1 ,43364   ,165,165,165
BEGIN DESCRIPTION:
Bitter Creek Trib14 71.2
END DESCRIPTION:
XS GIS Cut Line= 3
      1394391.25      6821544.94      1394456.47      6821333.99
      1394537.96      6821063.81
#Sta/Elev= 30
  4779.2 2346.23  4870.2 2345.26  4946.5 2342.33  4964.4 2342.55  4979.1 2341.14
  4985.3  2336.2  4989.9 2313.01  4990.4 2312.51  5000.7 2313.01  5006.3  2313.8
  5027.1 2313.94  5037.6 2315.13  5044.8 2317.05  5050.1 2316.91  5077.8 2320.22
  5100.3 2319.77  5110.7 2321.19  5131.6 2331.95    5149  2333.9  5154.2 2338.42
  5162.9 2337.98  5173.4 2338.89  5194.3 2343.75  5204.7 2345.36  5212.4 2345.11
    5215 2345.02    5220 2346.67  5225.6 2346.37  5258.4 2349.62  5282.2 2349.94
#Mann= 5 ,-1 , 0
  4779.2    .035       0  4989.9    .035       0  5000.7    .035       0
  5212.4     .16       0    5220     .07       0
Bank Sta=4989.9,5000.7
XS Rating Curve= 0 ,0
Exp/Cntr=0.3,0.1

Type RM Length L Ch R = 1 ,43199   ,186,186,186
BEGIN DESCRIPTION:
Bitter Creek Trib14 71.1
END DESCRIPTION:
XS GIS Cut Line= 3
      1394591.04      6821538.82      1394620.18      6821338.43
      1394681.86      6821143.87
#Sta/Elev= 30
  4797.5 2340.14  4819.6 2339.65  4848.9 2339.99  4869.1 2336.45  4889.3 2335.25
  4909.5 2335.86  4918.2 2334.03  4919.1 2333.84    4927 2333.56    4932 2331.29
  4939.8  2332.5  4949.9 2331.41    4960  2326.7  4980.2 2320.63  4990.3 2314.85
  4997.1 2312.17  5002.8 2312.56  5005.5 2311.53    5006 2311.03  5016.3 2311.53
  5042.4 2312.39  5067.1 2315.31  5084.4 2324.04  5094.1 2332.32  5099.4 2333.15
  5105.4 2340.27  5115.8 2344.77  5131.7 2347.65  5203.2 2349.12  5204.1 2349.12
#Mann= 7 ,-1 , 0
  4797.5     .07       0  4819.6    .035       0  4918.2     .07       0
  4919.1     .16       0  5005.5     .07       0  5016.3     .16       0
  5203.2     .07       0
Bank Sta=5005.5,5016.3
XS Rating Curve= 0 ,0
Exp/Cntr=0.3,0.1

Type RM Length L Ch R = 1 ,43013   ,422,422,422
BEGIN DESCRIPTION:
Bitter Creek Trib14 71.0
END DESCRIPTION:
XS GIS Cut Line= 3
      1394742.79       6821583.8      1394781.88      6821314.02
      1394805.01       6821134.2
#Sta/Elev= 30
  4727.4 2337.17  4773.2 2335.09  4790.6  2332.2  4848.4 2320.81  4884.8 2317.18
    4905 2316.15  4925.2 2313.12  4965.7 2311.62  4983.8    2310    5000 2310.13
  5000.6 2309.56  5001.1 2309.06  5011.5 2309.56  5016.1 2310.49  5026.2 2332.08
  5036.3 2330.19  5046.4 2331.83  5056.5 2334.72  5062.6 2334.91  5067.6 2336.87
  5076.6 2337.77  5086.7 2337.05  5096.8 2337.37    5117 2339.92  5127.1 2342.05
  5142.1 2341.91  5154.7 2346.13  5157.3 2346.95  5167.4 2346.64  5181.3 2347.36
#Mann= 5 ,-1 , 0
  4727.4     .07       0  4790.6     .16       0  5000.6     .07       0
  5011.5     .16       0  5154.7     .07       0
Bank Sta=5000.6,5011.5
XS Rating Curve= 0 ,0
Exp/Cntr=0.3,0.1