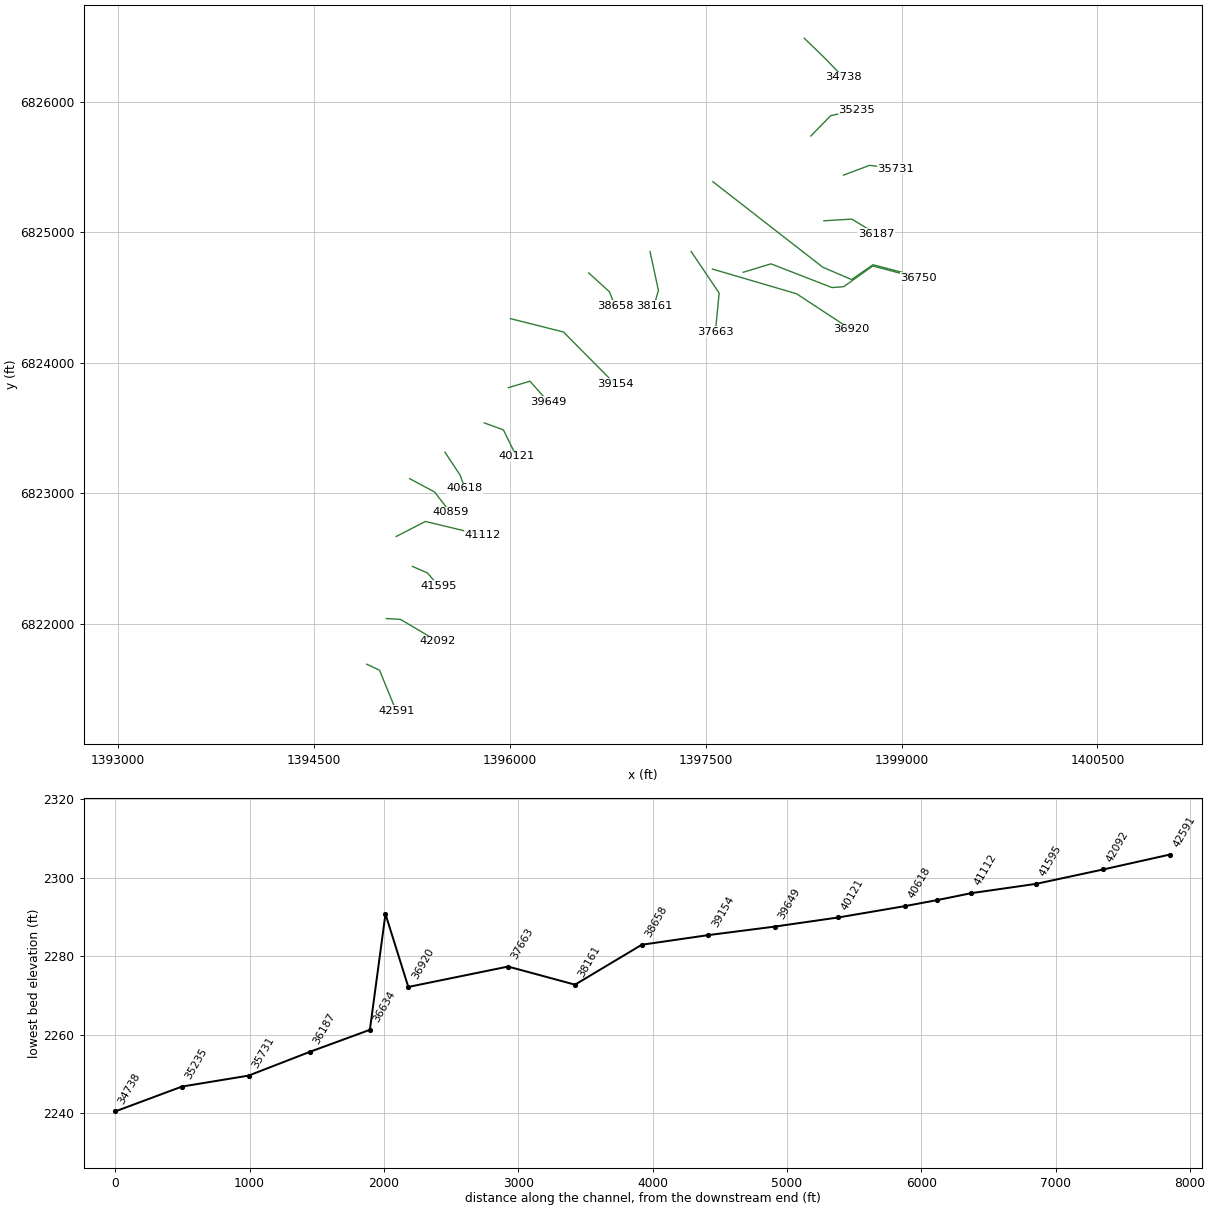
HEC-RAS study Bitter Creek Trib14.prj: Bitter Creek Trib14 Base Level Engineering

--- Bitter Creek Trib14.g01 (geometry) --- (continued)

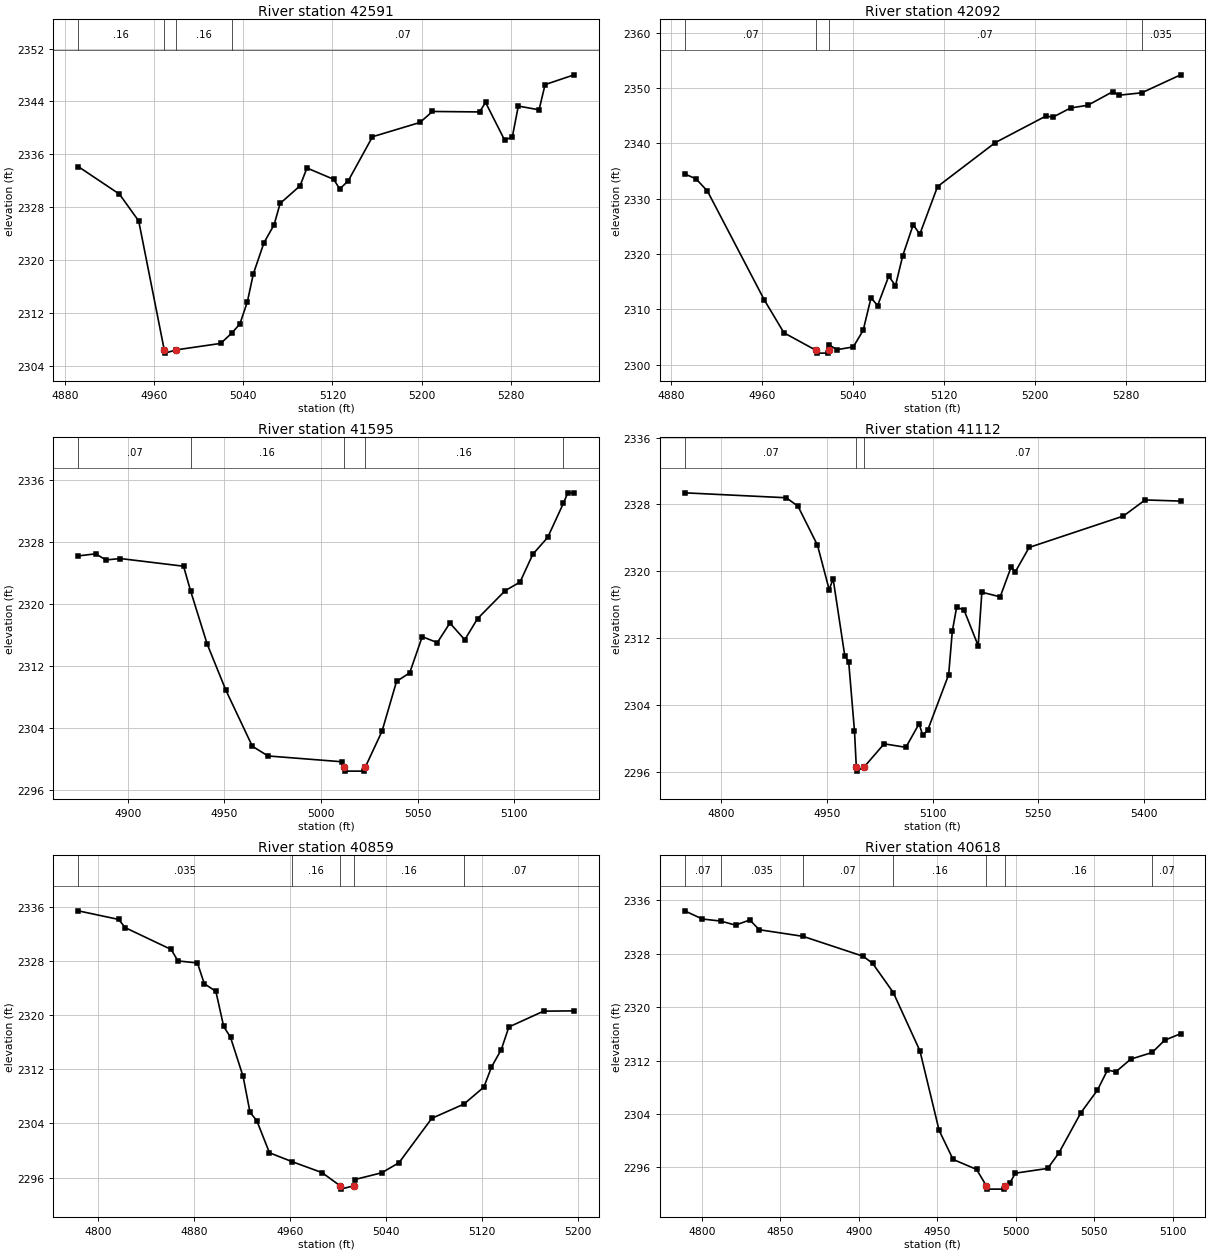
Type RM Length L Ch R = 1 ,42591   ,499,499,499
BEGIN DESCRIPTION:
Bitter Creek Trib14 70.0
END DESCRIPTION:
XS GIS Cut Line= 3
        1394905.        6821688.      1395002.99      6821642.13
      1395130.41      6821330.25
#Sta/Elev= 30
  4891.8 2334.14  4928.8 2329.96  4946.1 2325.89    4969 2306.38  4969.5 2305.88
    4980 2306.38  5019.6 2307.35  5029.4 2308.87  5036.9  2310.3  5043.6 2313.65
    5049  2317.9  5058.5 2322.59  5067.6 2325.32    5073 2328.55  5090.9 2331.22
  5097.1 2333.92  5121.1  2332.2  5126.5 2330.75  5134.1 2331.96  5155.9 2338.65
  5198.6 2340.82  5209.7 2342.48    5252 2342.41  5257.4 2343.85  5274.5 2338.14
  5281.4 2338.62  5286.8  2343.3  5305.4 2342.73  5310.8 2346.55  5336.9 2348.03
#Mann= 4 ,-1 , 0
  4891.8     .16       0    4969     .07       0    4980     .16       0
  5029.4     .07       0
Bank Sta=4969,4980
XS Rating Curve= 0 ,0
Exp/Cntr=0.3,0.1

Type RM Length L Ch R = 1 ,42092   ,497,497,497
BEGIN DESCRIPTION:
Bitter Creek Trib14 69.0
END DESCRIPTION:
XS GIS Cut Line= 3
      1395055.01        6822038.      1395163.14      6822031.94
      1395445.22      6821864.77
#Sta/Elev= 30
  4891.7 2334.46  4901.7 2333.57  4911.7 2331.36  4961.8 2311.66    4979 2305.74
  5007.3 2302.57  5007.8 2302.07  5017.8 2302.07  5018.3 2302.57  5018.6 2303.61
  5025.4 2302.69    5040 2303.19  5048.7 2306.19  5055.6 2312.07  5061.4 2310.66
  5071.2 2315.99  5077.1 2314.25  5083.5 2319.68  5092.7 2325.28  5098.5 2323.56
  5114.1 2332.17  5164.9 2340.12  5209.6 2344.94  5215.4  2344.7  5231.1 2346.38
  5246.3 2346.87  5268.1 2349.31  5273.9 2348.69  5293.7 2349.12  5327.9 2352.37
#Mann= 4 ,-1 , 0
  4891.7     .07       0  5007.3     .07       0  5018.3     .07       0
  5293.7    .035       0
Bank Sta=5007.3,5018.3
XS Rating Curve= 0 ,0
Exp/Cntr=0.3,0.1

Type RM Length L Ch R = 1 ,41595   ,483,483,483
BEGIN DESCRIPTION:
Bitter Creek Trib14 68.0
END DESCRIPTION:
XS GIS Cut Line= 3
        1395255.        6822438.      1395370.13      6822387.78
        1395455.        6822288.
#Sta/Elev= 30
  4874.4 2326.22  4883.4 2326.49  4888.8  2325.7  4896.2 2325.88  4928.9 2324.89
  4932.5 2321.74  4941.1 2314.85  4950.8 2308.87  4964.5 2301.63  4972.6 2300.38
  5010.8 2299.63  5011.8 2298.92  5012.3 2298.42  5022.4 2298.42  5022.9 2298.92
  5031.6 2303.58  5039.1 2310.01  5045.9 2311.11  5052.4 2315.79  5060.2 2315.02
  5066.7 2317.55  5074.4 2315.39    5081 2318.11  5095.3 2321.73    5103 2322.84
  5109.6 2326.43  5117.3 2328.61  5125.4    2333  5127.7 2334.37    5131 2334.37
#Mann= 5 ,-1 , 0
  4874.4     .07       0  4932.5     .16       0  5011.8     .07       0
  5022.9     .16       0  5125.4     .07       0
Bank Sta=5011.8,5022.9
XS Rating Curve= 0 ,0
Exp/Cntr=0.3,0.1

Type RM Length L Ch R = 1 ,41112   ,253,253,253
BEGIN DESCRIPTION:
Bitter Creek Trib14 67.0
END DESCRIPTION:
XS GIS Cut Line= 3
      1395130.96      6822667.36      1395354.52       6822782.8
       1395793.9      6822676.76
#Sta/Elev= 30
  4748.4 2329.38  4892.5 2328.79  4909.1 2327.78  4936.8 2323.11  4953.4 2317.79
    4959 2319.08  4975.5 2309.88  4981.1 2309.12  4989.3 2300.87  4991.9 2296.55
  4992.4 2296.05    5003 2296.55  5031.4 2299.32  5062.2  2298.9    5081 2301.72
  5086.2 2300.32  5093.1 2300.94  5122.9  2307.6  5128.1 2312.81  5134.2 2315.65
  5144.5 2315.39  5164.8 2311.07    5170 2317.48    5196 2316.92  5211.8 2320.55
    5217 2319.85  5237.1 2322.84  5370.8  2326.6  5401.7 2328.53    5452 2328.39
#Mann= 3 ,-1 , 0
  4748.4     .07       0  4991.9     .07       0    5003     .07       0
Bank Sta=4991.9,5003
XS Rating Curve= 0 ,0
Exp/Cntr=0.3,0.1

Type RM Length L Ch R = 1 ,40859   ,241,241,241
BEGIN DESCRIPTION:
Bitter Creek Trib14 66.1
END DESCRIPTION:
XS GIS Cut Line= 3
      1395233.75      6823110.77      1395424.76      6823008.42
      1395544.97       6822852.1
#Sta/Elev= 30
  4783.3  2335.4    4817 2334.13  4822.7  2332.9  4860.9 2329.69  4866.5    2328
  4882.8  2327.7  4888.5 2324.64  4898.2  2323.5  4904.7 2318.32  4910.4 2316.72
  4920.9 2310.94  4926.7 2305.63  4932.3 2304.42  4942.9 2299.66  4961.9 2298.34
  4986.8 2296.73  5001.8 2294.79  5002.3 2294.29  5013.6 2294.79    5014  2295.7
  5036.7 2296.71    5051 2298.19  5078.4 2304.75  5105.2 2306.85  5121.9 2309.37
  5128.2 2312.32  5136.4 2314.91  5142.7 2318.24  5171.7 2320.58  5197.2 2320.62
#Mann= 5 ,-1 , 0
  4783.3    .035       0  4961.9     .16       0  5001.8     .07       0
  5013.6     .16       0  5105.2     .07       0
Bank Sta=5001.8,5013.6
XS Rating Curve= 0 ,0
Exp/Cntr=0.3,0.1

Type RM Length L Ch R = 1 ,40618   ,497,497,497
BEGIN DESCRIPTION:
Bitter Creek Trib14 66.0
END DESCRIPTION:
XS GIS Cut Line= 3
      1395504.42      6823313.41      1395620.36      6823137.12
        1395655.        6823038.
#Sta/Elev= 30
    4789 2334.42  4800.3 2333.19  4811.9 2332.89  4821.4 2332.28  4830.5 2333.05
  4836.5 2331.59  4864.4  2330.6  4902.8 2327.61  4908.8 2326.54  4921.9 2322.19
  4938.9 2313.45  4951.1 2301.56    4960  2297.2    4975  2295.7  4981.2 2293.25
  4981.7 2292.75  4992.5 2292.75    4993 2293.25  4996.2 2293.67  4999.7 2295.14
  5020.3 2295.85  5027.4 2298.15  5041.4 2304.17    5052 2307.57  5058.4 2310.58
  5063.7 2310.31  5073.2 2312.21  5086.9 2313.21  5094.8 2315.04    5105 2316.02
#Mann= 7 ,-1 , 0
    4789     .07       0  4811.9    .035       0  4864.4     .07       0
  4921.9     .16       0  4981.2     .07       0    4993     .16       0
  5086.9     .07       0
Bank Sta=4981.2,4993
XS Rating Curve= 0 ,0
Exp/Cntr=0.3,0.1

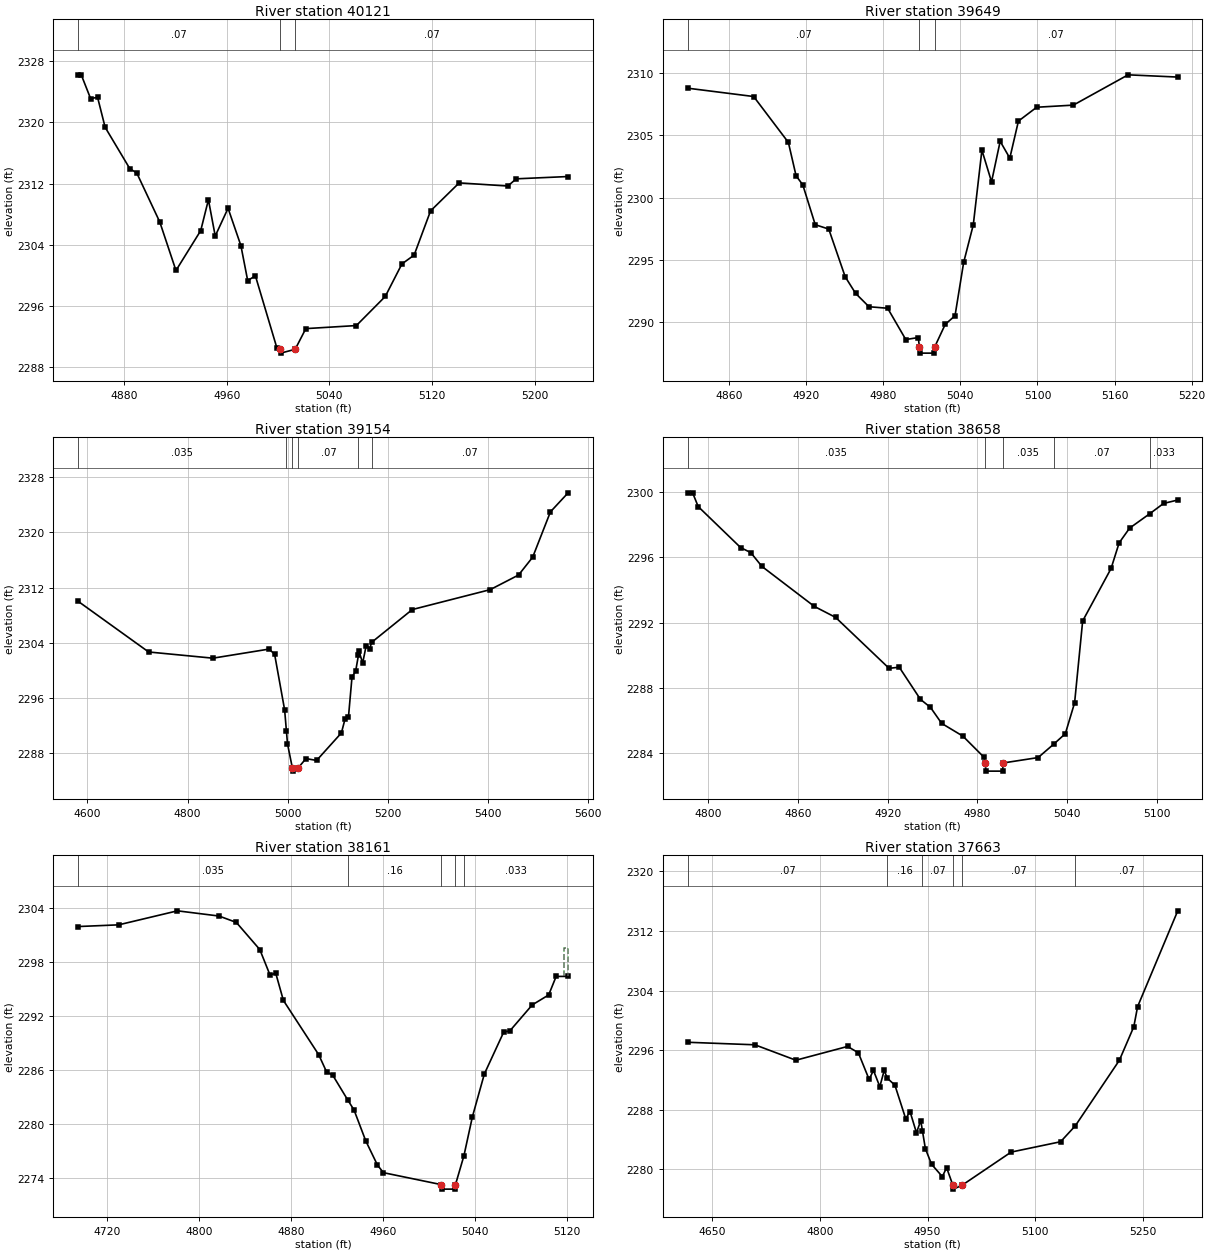
Type RM Length L Ch R = 1 ,40121   ,472,472,472
BEGIN DESCRIPTION:
Bitter Creek Trib14 65.0
END DESCRIPTION:
XS GIS Cut Line= 3
      1395805.04      6823537.99      1395951.65      6823484.68
      1396051.15      6823281.76
#Sta/Elev= 30
    4844  2326.2  4846.6  2326.2  4853.9 2323.09  4859.3 2323.27  4865.2 2319.35
  4884.5 2313.93  4889.8  2313.4  4907.8 2306.98  4920.4 2300.65  4939.7 2305.86
  4945.7 2309.89    4951 2305.15    4961 2308.78    4971  2303.9  4976.3 2299.33
  4982.3 2299.96  4999.1 2290.51  5001.5 2290.36    5002 2289.86  5013.3 2290.36
  5021.6 2293.06    5061 2293.46  5083.5 2297.26  5096.5 2301.51    5106 2302.66
  5118.8 2308.43  5141.1 2312.09    5179 2311.68  5185.6 2312.62    5226 2312.92
#Mann= 3 ,-1 , 0
    4844     .07       0  5001.5     .07       0  5013.3     .07       0
Bank Sta=5001.5,5013.3
XS Rating Curve= 0 ,0
Exp/Cntr=0.3,0.1

Type RM Length L Ch R = 1 ,39649   ,495,495,495
BEGIN DESCRIPTION:
Bitter Creek Trib14 64.0
END DESCRIPTION:
XS GIS Cut Line= 3
      1395989.92      6823808.39      1396154.68      6823858.13
      1396293.46      6823701.73
#Sta/Elev= 30
  4827.9 2308.79  4879.3 2308.12  4906.3 2304.44  4912.3 2301.76  4917.5 2301.04
  4927.2 2297.84  4937.7 2297.49  4950.5 2293.66  4958.6 2292.33    4969 2291.26
  4983.5 2291.14  4997.6 2288.63  5007.4 2288.79  5008.1 2288.04  5008.6 2287.54
  5019.6 2287.54  5020.1 2288.04  5028.3 2289.85  5035.9 2290.54  5042.6 2294.81
  5050.1 2297.83  5056.8 2303.82  5064.3 2301.28    5071 2304.53  5078.5 2303.18
  5085.2 2306.15  5099.4 2307.26  5127.9 2307.43  5170.5 2309.86  5209.1 2309.68
#Mann= 3 ,-1 , 0
  4827.9     .07       0  5008.1     .07       0  5020.1     .07       0
Bank Sta=5008.1,5020.1
XS Rating Curve= 0 ,0
Exp/Cntr=0.3,0.1

Type RM Length L Ch R = 1 ,39154   ,496,496,496
BEGIN DESCRIPTION:
Bitter Creek Trib14 63.0
END DESCRIPTION:
XS GIS Cut Line= 3
      1396004.99        6824338.      1396411.04      6824235.47
      1396804.98      6823838.02
#Sta/Elev= 30
  4581.2 2310.02  4722.3 2302.65  4850.6 2301.75  4962.8 2303.07  4973.8 2302.31
  4993.8 2294.24  4997.4 2291.14  4999.5 2289.33  5009.1 2285.87  5009.6 2285.37
  5021.1 2285.87  5036.4 2287.19  5057.6 2286.92  5107.1 2290.91  5114.1 2292.86
  5121.2 2293.24  5128.3 2299.06  5135.4 2299.82  5141.1 2302.18  5142.4 2302.72
  5149.5 2301.04  5156.6 2303.58  5163.7 2303.11  5167.2 2304.03  5248.5  2308.8
  5404.1 2311.69  5460.7 2313.81  5488.9  2316.4  5524.3 2322.97  5559.6 2325.73
#Mann= 6 ,-1 , 0
  4581.2    .035       0  4997.4     .07       0  5009.1     .07       0
  5021.1     .07       0  5141.1     .16       0  5167.2     .07       0
Bank Sta=5009.1,5021.1
XS Rating Curve= 0 ,0
Exp/Cntr=0.3,0.1

Type RM Length L Ch R = 1 ,38658   ,497,497,497
BEGIN DESCRIPTION:
Bitter Creek Trib14 62.0
END DESCRIPTION:
XS GIS Cut Line= 3
      1396604.97      6824688.03      1396763.16      6824544.05
        1396805.        6824438.
#Sta/Elev= 30
  4786.1 2299.94  4789.5 2299.94  4793.2  2299.1  4821.6 2296.59  4828.4 2296.28
  4835.8 2295.44  4870.9 2292.99  4885.1 2292.32  4920.9  2289.2  4927.7 2289.27
  4941.9  2287.3  4948.6 2286.81  4956.1 2285.83  4970.3 2285.05  4984.5 2283.75
  4985.2 2283.41  4985.7 2282.91  4996.8 2282.91  4997.3 2283.41  5020.6 2283.74
  5030.9 2284.55  5038.8  2285.2    5045 2287.09  5050.4  2292.1  5069.4 2295.31
  5074.8 2296.88  5081.8 2297.78  5095.4 2298.67  5104.5 2299.29    5114  2299.5
#Mann= 5 ,-1 , 0
  4786.1    .035       0  4985.2    .035       0  4997.3    .035       0
  5030.9     .07       0  5095.4    .033       0
Bank Sta=4985.2,4997.3
XS Rating Curve= 0 ,0
Exp/Cntr=0.3,0.1

Type RM Length L Ch R = 1 ,38161   ,498,498,498
BEGIN DESCRIPTION:
Bitter Creek Trib14 61.0
END DESCRIPTION:
XS GIS Cut Line= 3
      1397074.12       6824852.6       1397138.3      6824554.32
        1397105.        6824438.
#Sta/Elev= 30
  4694.9 2301.97  4730.3 2302.16  4781.4 2303.72  4817.6 2303.14  4832.6 2302.43
    4853 2299.41  4861.8  2296.6  4866.9 2296.76  4873.5 2293.75  4904.2 2287.71
  4911.1 2285.78  4916.3 2285.45  4929.4 2282.68  4934.9 2281.56  4945.1 2278.12
  4955.3 2275.42  4960.5 2274.58  5010.8 2273.25  5011.3 2272.75  5022.6 2272.75
  5023.1 2273.25  5030.4 2276.45  5037.8  2280.8  5048.2 2285.57  5065.1 2290.25
  5070.3 2290.35  5089.8 2293.25  5104.1 2294.36  5110.6 2296.42    5121 2296.42
#Mann= 5 ,-1 , 0
  4694.9    .035       0  4929.4     .16       0  5010.8     .07       0
  5023.1     .16       0  5030.4    .033       0
#XS Ineff= 2 , 0
                         5117.77          2299.6
Permanent Ineff=
       F       F
Bank Sta=5010.8,5023.1
XS Rating Curve= 0 ,0
Exp/Cntr=0.3,0.1

Type RM Length L Ch R = 1 ,37663   ,743,743,743
BEGIN DESCRIPTION:
Bitter Creek Trib14 60.0
END DESCRIPTION:
XS GIS Cut Line= 3
      1397388.78      6824852.62      1397603.37      6824534.06
      1397574.65      6824237.04
#Sta/Elev= 30
  4615.9 2297.07  4709.7 2296.73  4766.7 2294.66  4838.7 2296.51  4853.7 2295.66
  4868.7 2292.08  4874.7  2293.3  4883.6 2291.11  4889.7  2293.3  4893.9 2292.26
  4904.6 2291.31  4919.6 2286.82  4925.7 2287.75  4934.6 2284.93  4940.6 2286.55
  4942.9  2285.2    4947  2282.8  4955.6  2280.7  4970.6 2279.04  4976.6 2280.23
  4985.4 2277.86  4985.9 2277.36  4997.8 2277.86  5066.4 2282.33  5135.3 2283.72
  5155.8 2285.86  5217.1 2294.65  5237.2 2299.15  5242.5 2301.85  5298.4 2314.71
#Mann= 6 ,-1 , 0
  4615.9     .07       0  4893.9     .16       0  4942.9     .07       0
  4985.4    .033       0  4997.8     .07       0  5155.8     .07       0
Bank Sta=4985.4,4997.8
XS Rating Curve= 0 ,0
Exp/Cntr=0.3,0.1

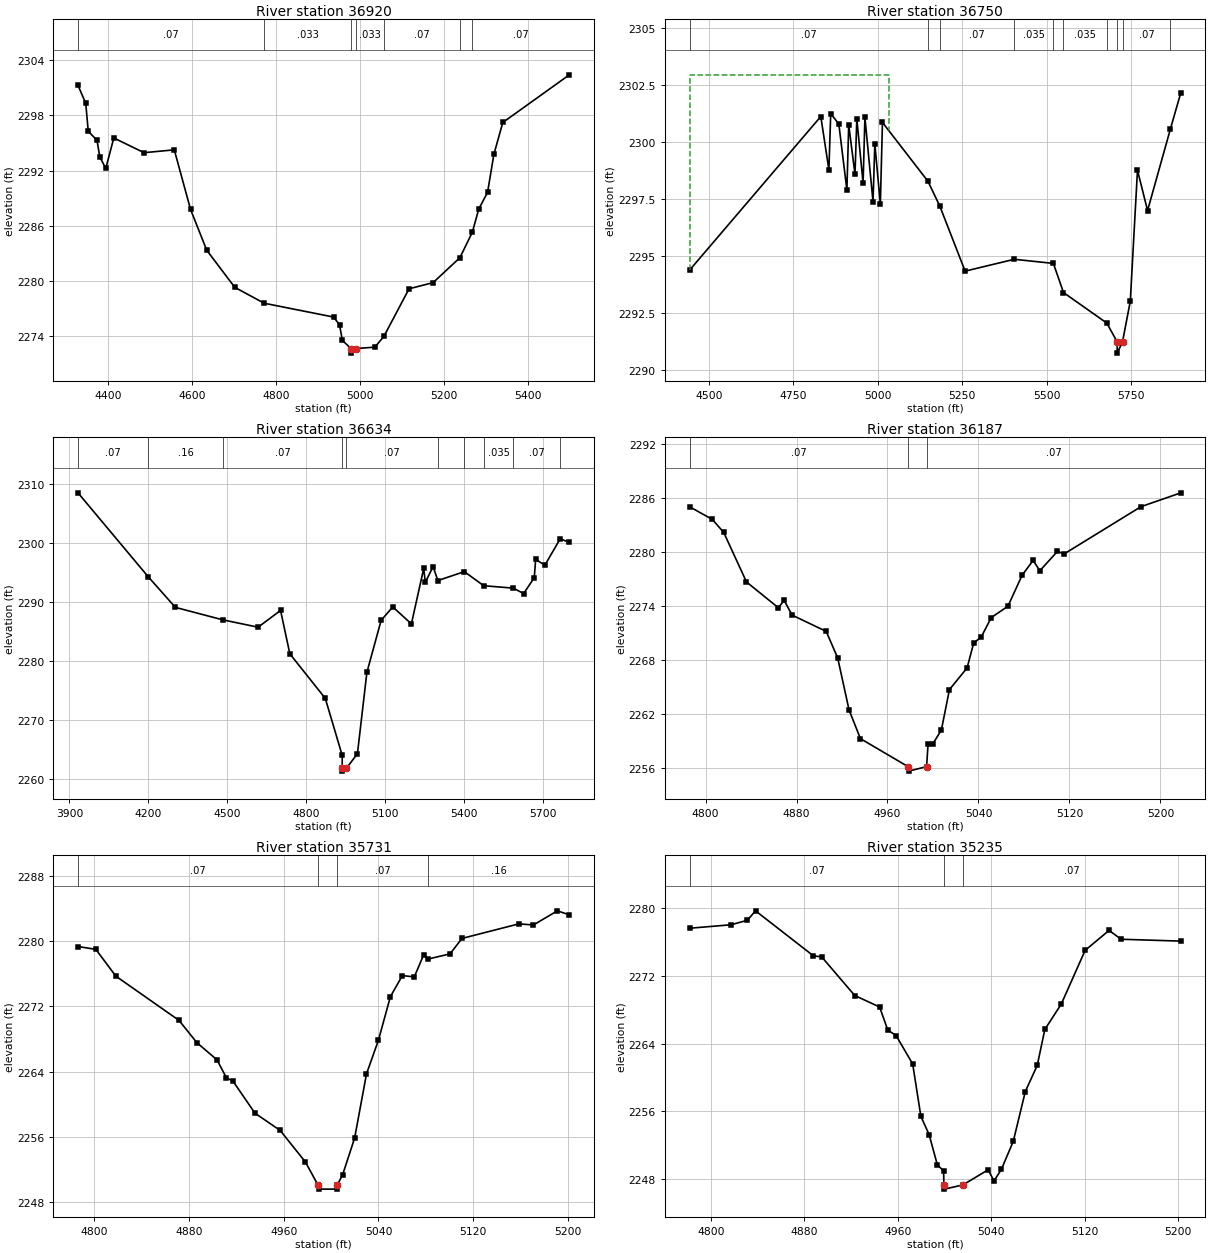
Type RM Length L Ch R = 1 ,36920   ,170,170,170
BEGIN DESCRIPTION:
Bitter Creek Trib14 59.0
END DESCRIPTION:
XS GIS Cut Line= 3
       1397551.6      6824718.03      1398195.75      6824528.69
      1398611.56      6824255.55
#Sta/Elev= 30
  4328.6 2301.27  4347.1 2299.31    4353 2296.27  4373.8 2295.31  4380.5 2293.49
  4394.7 2292.24  4413.8 2295.55  4485.8 2293.95  4557.7 2294.26  4596.3  2287.8
  4634.9 2283.35  4701.6 2279.32  4771.6 2277.59  4936.7 2276.09  4950.8 2275.25
  4957.5 2273.56    4978 2272.67  4978.5 2272.17  4990.4 2272.67    5035 2272.82
  5056.6 2274.01  5116.2 2279.16  5173.4 2279.83  5237.2 2282.54  5266.9 2285.32
  5281.9 2287.81    5303 2289.64  5318.1 2293.78  5339.2 2297.23  5497.5 2302.41
#Mann= 7 ,-1 , 0
  4328.6     .07       0  4771.6    .033       0    4978    .033       0
  4990.4    .033       0  5056.6     .07       0  5237.2    .035       0
  5266.9     .07       0
Bank Sta=4978,4990.4
XS Rating Curve= 0 ,0
Exp/Cntr=0.3,0.1

Type RM Length L Ch R = 1 ,36750   ,116,116,116
BEGIN DESCRIPTION:
Bitter Creek Trib14 4272
END DESCRIPTION:
XS GIS Cut Line= 6
      1397787.68      6824693.32      1397999.79      6824757.97
      1398467.07      6824576.12      1398556.92      6824582.63
      1398779.57      6824741.49      1399129.82      6824649.04
#Sta/Elev= 30
  4441.9 2294.38  4830.9 2301.13  4854.9 2298.79  4860.3 2301.26  4884.3  2300.8
  4908.2  2297.9  4913.6 2300.77  4932.2 2298.59  4937.6 2301.02  4956.2 2298.21
  4961.6 2301.09  4985.6 2297.39    4991 2299.93  5007.3 2297.28  5013.6 2300.87
  5148.2 2298.29  5183.4  2297.2  5258.5 2294.34  5404.1 2294.86    5520 2294.68
    5550  2293.4  5678.3 2292.06  5708.8 2291.24  5709.3 2290.74  5724.9 2291.24
  5747.9 2293.02  5769.2 2298.77  5799.1    2297  5866.7 2300.58  5897.7 2302.18
#Mann= 10 ,-1 , 0
  4441.9     .07       0  5148.2    .035       0  5183.4     .07       0
  5404.1    .035       0    5520     .07       0    5550    .035       0
  5678.3     .07       0  5708.8     .07       0  5724.9     .07       0
  5866.7     .16       0
#XS Ineff= 2 , 0
          5033.5 2302.96
Permanent Ineff=
       F       F
Bank Sta=5708.8,5724.9
XS Rating Curve= 0 ,0
Exp/Cntr=0.3,0.1

Type RM Length L Ch R = 1 ,36634   ,447,447,447
BEGIN DESCRIPTION:
Bitter Creek Trib14 58.0
END DESCRIPTION:
XS GIS Cut Line= 5
      1397554.97      6825388.03      1398396.91      6824731.92
      1398617.77      6824637.35      1398781.11      6824750.99
      1399130.11       6824659.6
#Sta/Elev= 30
  3932.6 2308.42  4198.9 2294.23  4302.7 2289.01  4483.5 2286.89  4617.2 2285.65
  4702.5 2288.49  4737.8 2281.14  4872.6 2273.58  4936.8 2263.92  4936.9 2261.76
  4937.4 2261.26    4953 2261.76  4994.7 2264.21  5030.6 2277.99  5084.9 2286.83
  5129.1 2289.08  5199.8 2286.21  5246.6 2295.61  5252.7 2293.25  5282.3 2295.93
  5300.4 2293.55  5400.9 2295.07  5474.6 2292.68  5586.9 2292.27  5626.4 2291.35
  5666.8 2294.05    5672 2297.13  5707.2 2296.16  5765.3 2300.64    5800 2300.01
#Mann= 10 ,-1 , 0
  3932.6     .07       0  4198.9     .16       0  4483.5     .07       0
  4936.9     .07       0    4953     .07       0  5300.4    .035       0
  5400.9     .07       0  5474.6    .035       0  5586.9     .07       0
  5765.3     .16       0
Bank Sta=4936.9,4953
XS Rating Curve= 0 ,0
Exp/Cntr=0.3,0.1

Type RM Length L Ch R = 1 ,36187   ,456,456,456
BEGIN DESCRIPTION:
Bitter Creek Trib14 57.0
END DESCRIPTION:
XS GIS Cut Line= 3
      1398404.99        6825088.      1398618.68      6825101.19
        1398805.        6824988.
#Sta/Elev= 30
  4785.9 2285.02  4805.9 2283.61    4816 2282.16    4836 2276.66  4864.1 2273.79
  4869.1 2274.63  4876.1 2272.98  4906.1 2271.17  4916.2 2268.23  4926.2 2262.45
  4936.2 2259.26  4978.1 2256.15  4978.6 2255.65  4994.4 2256.15  4995.7  2258.7
    5000  2258.7  5007.4 2260.22  5014.5 2264.71    5030 2267.11  5035.8 2269.87
  5042.5 2270.56  5051.3 2272.71  5065.9 2273.96  5078.5 2277.43  5088.1 2279.05
    5094 2277.91  5109.5 2280.06  5115.3 2279.77  5182.9 2285.02    5218 2286.56
#Mann= 3 ,-1 , 0
  4785.9     .07       0  4978.1     .07       0  4994.4     .07       0
Bank Sta=4978.1,4994.4
XS Rating Curve= 0 ,0
Exp/Cntr=0.3,0.1

Type RM Length L Ch R = 1 ,35731   ,496,496,496
BEGIN DESCRIPTION:
Bitter Creek Trib14 56.0
END DESCRIPTION:
XS GIS Cut Line= 3
      1398555.02      6825438.01      1398755.29      6825513.12
      1398955.02        6825488.
#Sta/Elev= 30
  4786.1 2279.31  4801.2 2278.96  4818.1 2275.68  4871.5 2270.26  4886.6 2267.53
  4903.6 2265.43  4911.6 2263.21  4916.9 2262.86  4935.6 2258.91    4957 2256.78
  4978.3 2252.92  4988.9  2250.1  4989.4  2249.6  5004.7  2249.6  5005.2  2250.1
  5009.8 2251.38  5019.9 2255.87  5029.9 2263.71    5040 2267.84  5050.1 2273.17
  5060.2 2275.75  5070.3 2275.59  5078.2 2278.29  5082.1 2277.78  5100.5 2278.41
  5110.6  2280.3  5158.6 2282.08    5171 2281.95  5191.2 2283.68  5201.3 2283.19
#Mann= 4 ,-1 , 0
  4786.1     .07       0  4988.9     .07       0  5005.2     .07       0
  5082.1     .16       0
Bank Sta=4988.9,5005.2
XS Rating Curve= 0 ,0
Exp/Cntr=0.3,0.1

Type RM Length L Ch R = 1 ,35235   ,497,497,497
BEGIN DESCRIPTION:
Bitter Creek Trib14 55.0
END DESCRIPTION:
XS GIS Cut Line= 3
      1398304.99      6825737.99       1398457.5      6825894.03
      1398654.97      6825937.99
#Sta/Elev= 30
  4781.8 2277.65  4817.2 2278.06  4831.3 2278.59  4838.3 2279.71  4887.9 2274.38
  4894.9 2274.27  4923.2  2269.7  4944.5 2268.34  4951.5 2265.61  4958.6 2264.97
  4972.8  2261.6  4979.8 2255.42  4986.9 2253.24  4993.9 2249.68  4999.3 2248.96
  4999.5 2247.31    5000 2246.81  5015.8 2247.31  5037.3 2249.09  5042.4 2247.79
  5048.7 2249.14  5058.9 2252.47  5069.2 2258.35  5079.4 2261.44  5085.9 2265.69
  5099.9 2268.67  5120.4 2275.04  5140.9  2277.4  5151.1 2276.35  5202.3 2276.13
#Mann= 3 ,-1 , 0
  4781.8     .07       0  4999.5     .07       0  5015.8     .07       0
Bank Sta=4999.5,5015.8
XS Rating Curve= 0 ,0
Exp/Cntr=0.3,0.1

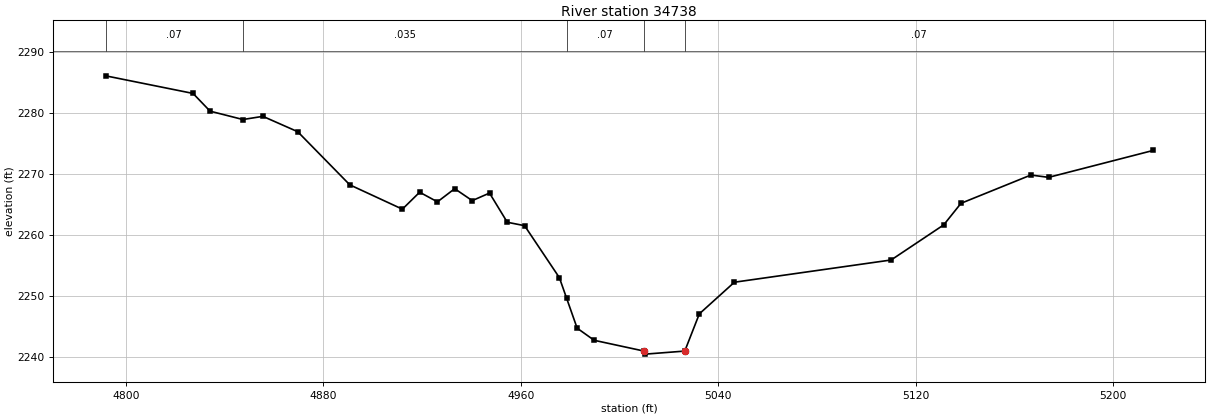
Type RM Length L Ch R = 1 ,34738   ,500,500,500
BEGIN DESCRIPTION:
Bitter Creek Trib14 54.0
END DESCRIPTION:
XS GIS Cut Line= 3
        1398255.        6826488.      1398404.58      6826343.17
      1398554.99      6826188.01
#Sta/Elev= 30
  4791.8 2286.15  4827.2 2283.26  4834.1 2280.35  4847.4 2278.98  4855.5  2279.5
  4869.6 2276.98  4890.7 2268.26    4912 2264.27    4919 2267.05  4926.2 2265.47
  4933.2 2267.63  4940.3 2265.67  4947.3 2266.91  4954.5 2262.12  4961.5 2261.56
  4975.6 2253.03  4978.5 2249.69  4982.8 2244.74  4989.7 2242.75  5009.9 2240.98
  5010.4 2240.48  5026.4 2240.98  5032.3 2247.09  5046.5 2252.28    5110 2255.93
  5131.3 2261.69  5138.3 2265.23  5166.6 2269.87  5173.8 2269.49  5216.1  2273.9
#Mann= 5 ,-1 , 0
  4791.8     .07       0  4847.4    .035       0  4978.5     .07       0
  5009.9     .07       0  5026.4     .07       0
Bank Sta=5009.9,5026.4
XS Rating Curve= 0 ,0
Exp/Cntr=0.3,0.1