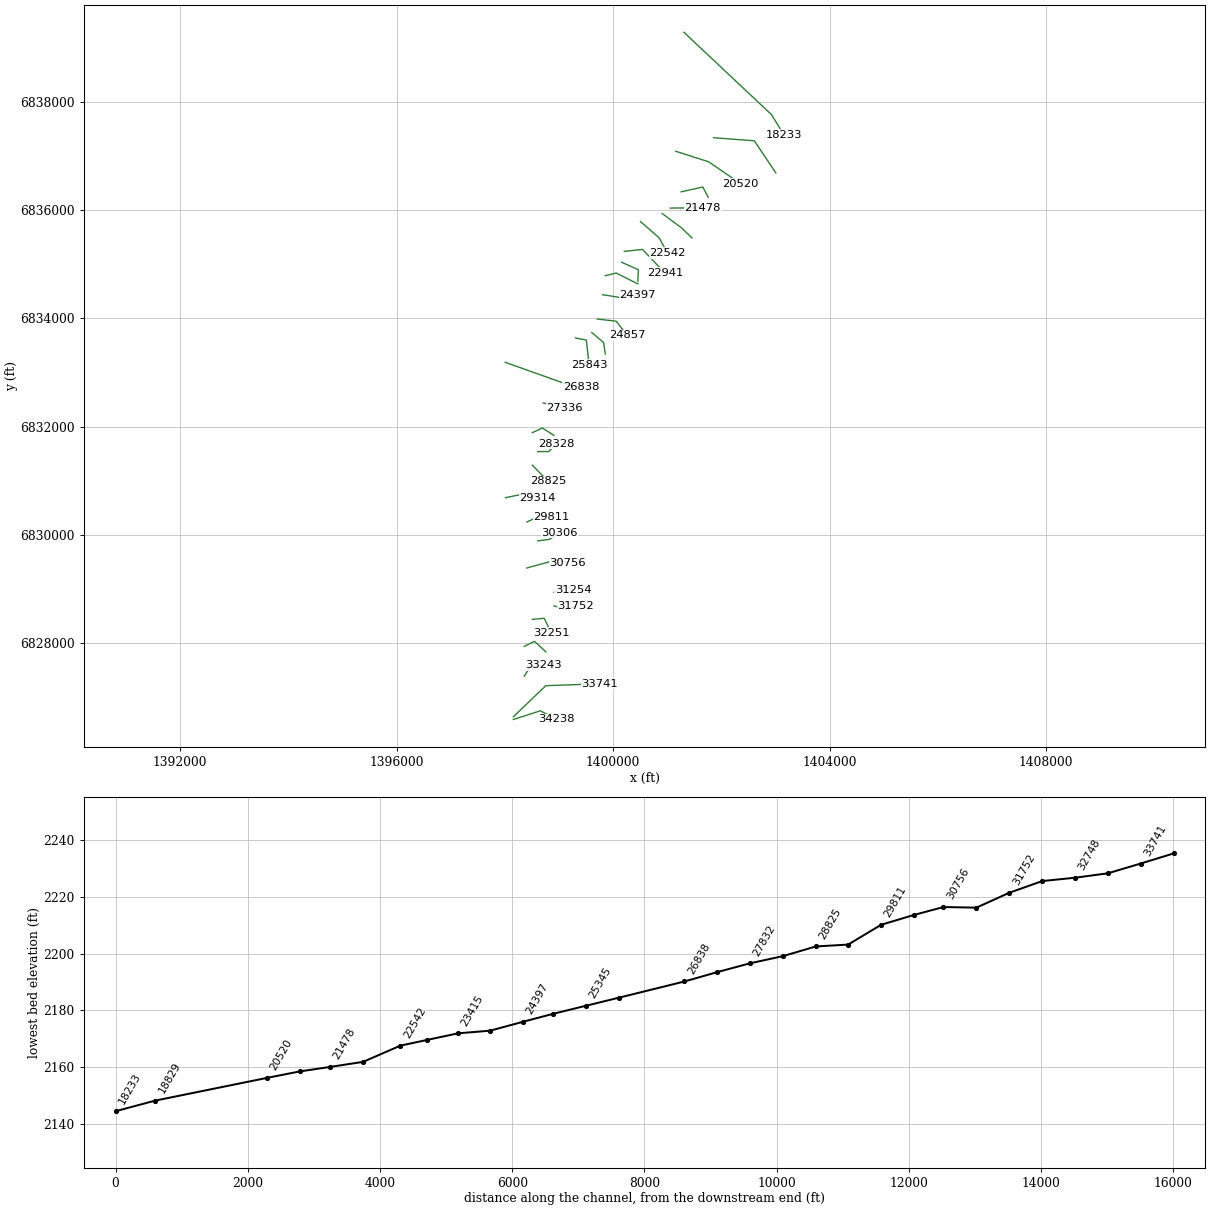
HEC-RAS study Bitter Creek Trib14.prj: Bitter Creek Trib14 Base Level Engineering

--- Bitter Creek Trib14.g01 (geometry) --- (continued)

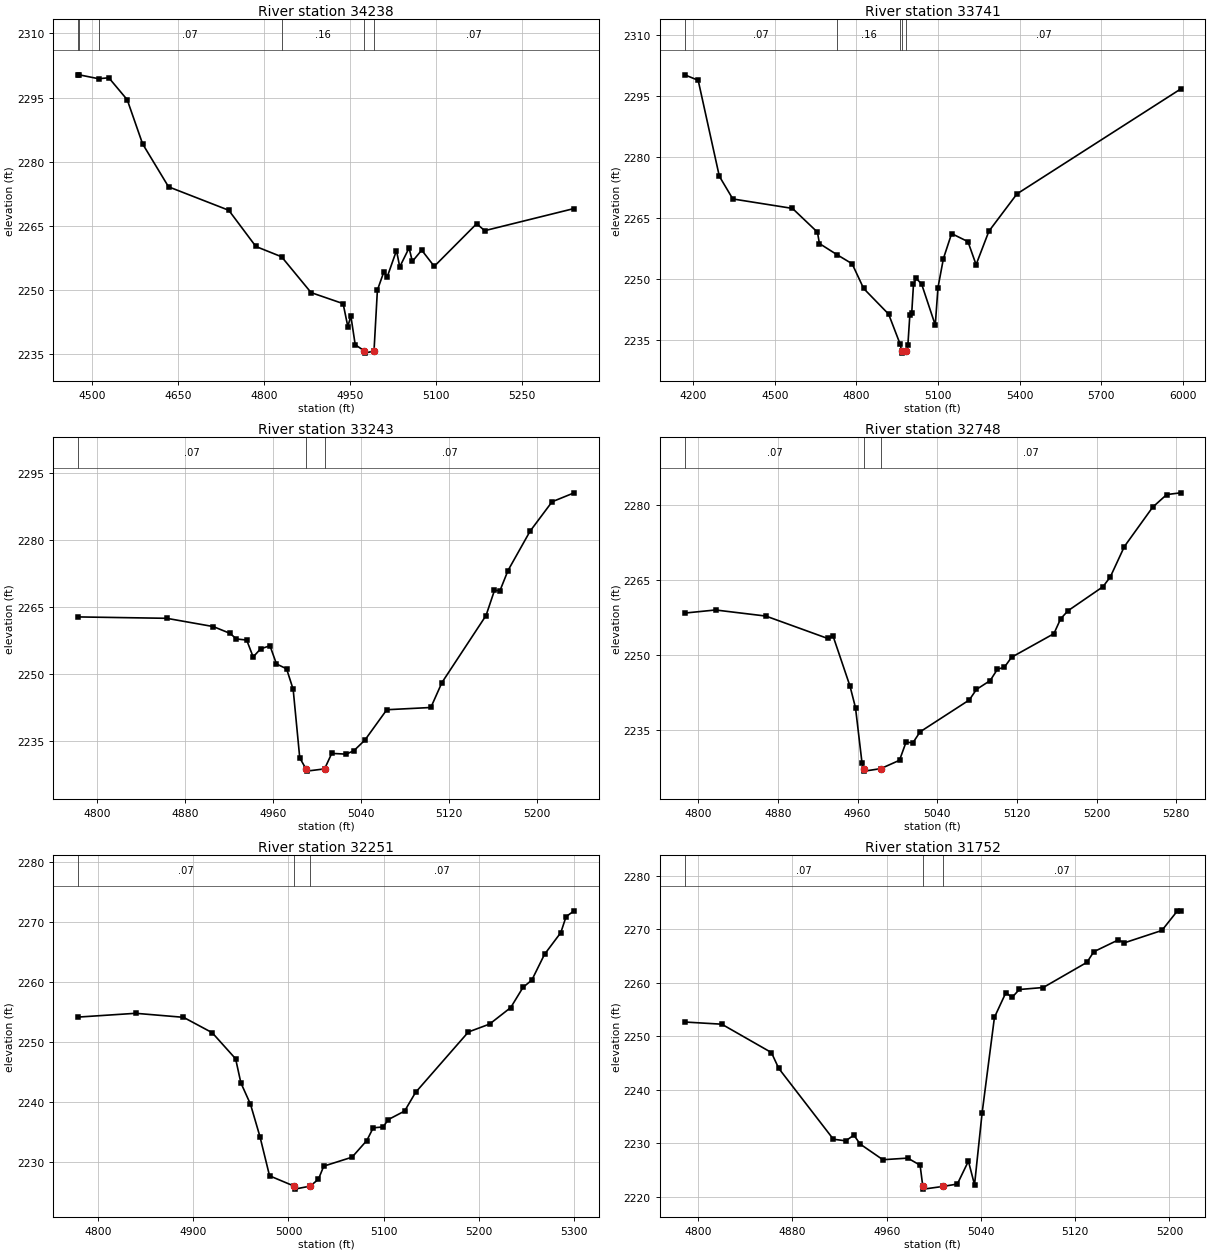
Type RM Length L Ch R = 1 ,34238   ,497,497,497
BEGIN DESCRIPTION:
Bitter Creek Trib14 53.0
END DESCRIPTION:
XS GIS Cut Line= 3
      1398154.97      6826587.99      1398653.78       6826748.5
      1398954.99      6826588.01
#Sta/Elev= 30
    4476 2300.31  4477.7 2300.31  4511.5  2299.4  4529.4 2299.62  4561.5 2294.49
  4588.3 2284.19  4633.6 2274.15  4738.7 2268.67    4786 2260.21  4830.8 2257.81
  4882.3 2249.44  4938.2 2246.86  4946.4 2241.52  4951.7 2243.98  4959.3 2237.26
  4975.5  2235.8    4976  2235.3  4992.1  2235.8    4998 2250.01  5009.4 2254.34
    5015 2253.05  5031.3 2259.27    5037 2255.44  5053.3 2259.88    5059 2256.72
  5075.3 2259.36  5097.2 2255.57  5171.3 2265.54  5185.1  2263.9  5341.3 2269.08
#Mann= 6 ,-1 , 0
    4476     .07       0  4477.7    .035       0  4511.5     .07       0
  4830.8     .16       0  4975.5     .07       0  4992.1     .07       0
Bank Sta=4975.5,4992.1
XS Rating Curve= 0 ,0
Exp/Cntr=0.3,0.1

Type RM Length L Ch R = 1 ,33741   ,498,498,498
BEGIN DESCRIPTION:
Bitter Creek Trib14 52.0
END DESCRIPTION:
XS GIS Cut Line= 3
      1398154.97      6826637.97      1398755.23      6827212.93
      1399746.22      6827247.52
#Sta/Elev= 30
  4168.8 2300.28  4218.4 2298.94  4296.1 2275.31  4345.7 2269.71    4565 2267.38
  4656.8 2261.53    4664 2258.73  4728.6 2255.99  4784.2 2253.75  4826.6 2247.66
  4918.4 2241.34  4960.4 2234.01  4966.6 2232.24  4967.1 2231.74  4983.5 2232.24
  4989.2  2233.8  4996.4 2241.14  5003.4 2241.73  5009.8 2248.73  5019.8 2250.17
  5039.8 2248.72  5089.8 2238.65  5099.8 2247.88  5119.8 2255.04  5149.9 2261.18
  5209.9  2259.2  5239.9 2253.53  5286.9 2261.76    5390 2270.95  5991.6 2296.78
#Mann= 5 ,-1 , 0
  4168.8     .07       0  4728.6     .16       0  4960.4     .07       0
  4966.6     .07       0  4983.5     .07       0
Bank Sta=4966.6,4983.5
XS Rating Curve= 0 ,0
Exp/Cntr=0.3,0.1

Type RM Length L Ch R = 1 ,33243   ,495,495,495
BEGIN DESCRIPTION:
Bitter Creek Trib14 51.0
END DESCRIPTION:
XS GIS Cut Line= 3
        1398355.        6827388.      1398471.43      6827571.23
      1398705.03        6827588.
#Sta/Elev= 30
  4782.9 2262.75  4863.4 2262.44  4905.7  2260.6    4921 2259.08  4926.9 2257.82
  4936.2 2257.58  4942.1  2253.8  4948.8  2255.6  4957.4 2256.31  4963.3 2252.24
  4972.5 2251.16  4978.5 2246.57  4984.5 2231.24  4990.2 2228.79  4990.7 2228.29
  5007.1 2228.79  5013.6 2232.25  5026.7 2232.09  5033.7 2232.84  5043.7  2235.2
  5063.7 2242.01  5103.8 2242.51  5113.9 2248.09    5154 2263.06  5161.7 2268.68
  5166.7 2268.62    5174 2273.12  5194.1 2281.91  5214.1 2288.48  5234.2 2290.48
#Mann= 3 ,-1 , 0
  4782.9     .07       0  4990.2     .07       0  5007.1     .07       0
Bank Sta=4990.2,5007.1
XS Rating Curve= 0 ,0
Exp/Cntr=0.3,0.1

Type RM Length L Ch R = 1 ,32748   ,497,497,497
BEGIN DESCRIPTION:
Bitter Creek Trib14 50.0
END DESCRIPTION:
XS GIS Cut Line= 3
      1398354.96      6827937.98       1398546.9      6828031.93
      1398755.03      6827837.97
#Sta/Elev= 30
  4786.3 2258.35  4817.3 2258.97  4867.9 2257.75  4929.9 2253.28  4935.4 2253.73
  4952.4 2243.72  4957.9 2239.42  4964.5 2228.29  4966.4 2227.24  4966.9 2226.74
  4983.3 2227.24  5002.1 2228.91  5008.7 2232.55  5015.5 2232.39  5022.8  2234.6
  5072.2 2240.97  5079.4 2243.08  5093.2 2244.85  5100.5 2247.13  5107.4  2247.5
  5114.7 2249.52  5157.2 2254.23    5164 2257.21  5171.4 2258.82  5206.5 2263.62
  5213.9 2265.59    5228 2271.66  5256.4 2279.52  5270.5 2282.05  5284.5  2282.4
#Mann= 3 ,-1 , 0
  4786.3     .07       0  4966.4     .07       0  4983.3     .07       0
Bank Sta=4966.4,4983.3
XS Rating Curve= 0 ,0
Exp/Cntr=0.3,0.1

Type RM Length L Ch R = 1 ,32251   ,499,499,499
BEGIN DESCRIPTION:
Bitter Creek Trib14 49.0
END DESCRIPTION:
XS GIS Cut Line= 3
        1398505.        6828438.      1398724.78      6828458.09
      1398854.98      6828188.04
#Sta/Elev= 30
  4779.3 2254.22  4839.6 2254.85  4889.8 2254.18  4919.9 2251.62  4944.5 2247.27
    4950 2243.27  4960.1  2239.7  4970.1 2234.27  4980.1 2227.78  5005.9 2226.06
  5006.4 2225.56  5022.8 2226.06  5031.4 2227.21    5037 2229.39  5066.7 2230.88
  5082.2 2233.66  5088.9 2235.77  5099.3 2235.92  5104.8 2237.15  5121.9 2238.57
  5133.3 2241.66  5188.8 2251.74    5211 2253.05  5233.2  2255.8  5246.1 2259.16
  5255.4 2260.39  5268.7 2264.67  5285.8 2268.29  5291.3 2270.95  5299.8 2271.92
#Mann= 3 ,-1 , 0
  4779.3     .07       0  5005.9     .07       0  5022.8     .07       0
Bank Sta=5005.9,5022.8
XS Rating Curve= 0 ,0
Exp/Cntr=0.3,0.1

Type RM Length L Ch R = 1 ,31752   ,498,498,498
BEGIN DESCRIPTION:
Bitter Creek Trib14 48.0
END DESCRIPTION:
XS GIS Cut Line= 3
      1398905.03      6828687.99      1399106.04      6828622.52
      1399305.04      6828688.01
#Sta/Elev= 30
  4788.6 2252.69  4820.1 2252.28  4862.2 2246.98  4868.4 2244.03  4914.8 2230.77
  4925.3 2230.47  4932.2 2231.54  4937.5 2229.87  4956.8 2226.94  4977.9 2227.24
  4988.4 2225.92  4990.7 2221.94  4991.2 2221.44  5007.7 2221.94    5020 2222.39
  5029.4 2226.67  5034.6 2222.26    5041 2235.64  5051.5 2253.57  5061.2 2258.18
  5066.4 2257.28  5072.6 2258.77  5092.9 2259.14    5130 2263.85  5135.8 2265.83
  5156.5 2268.03  5161.8  2267.5  5193.6 2269.81  5206.8 2273.48  5209.5 2273.48
#Mann= 3 ,-1 , 0
  4788.6     .07       0  4990.7     .07       0  5007.7     .07       0
Bank Sta=4990.7,5007.7
XS Rating Curve= 0 ,0
Exp/Cntr=0.3,0.1

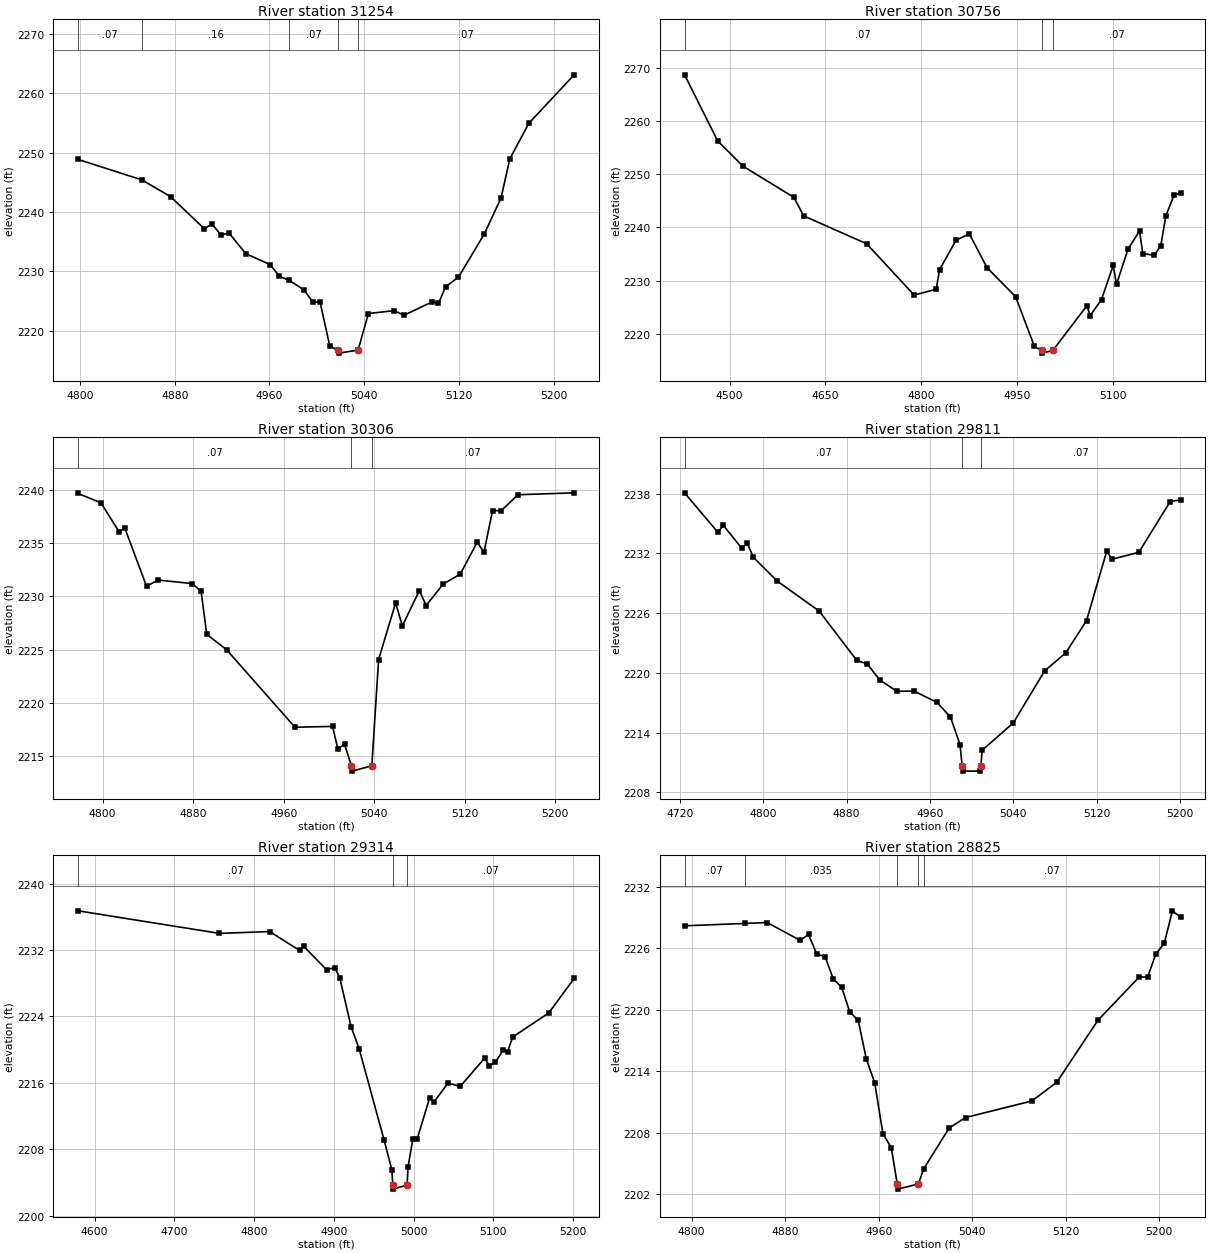
Type RM Length L Ch R = 1 ,31254   ,498,498,498
BEGIN DESCRIPTION:
Bitter Creek Trib14 47.0
END DESCRIPTION:
XS GIS Cut Line= 3
      1398905.03      6828938.03      1399054.84      6829072.94
      1399254.97      6828988.01
#Sta/Elev= 30
  4798.4 2248.85  4852.2 2245.41  4876.5 2242.58  4904.9 2237.19  4911.6 2237.94
  4919.1  2236.1  4925.8 2236.46    4940 2232.97  4960.9 2231.09  4968.4 2229.12
  4976.6 2228.49  4989.3 2226.83  4996.7 2224.79  5002.8 2224.79    5011 2217.36
  5017.9 2216.69  5018.4 2216.19  5034.9 2216.69  5043.6 2222.87  5065.3 2223.35
  5073.7 2222.59  5097.4 2224.82  5102.8 2224.57  5108.8 2227.37  5119.7 2229.01
  5141.4 2236.24  5155.6 2242.33  5163.1 2248.97  5179.2 2254.96  5217.4 2263.12
#Mann= 5 ,-1 , 0
  4798.4     .07       0  4852.2     .16       0  4976.6     .07       0
  5017.9     .07       0  5034.9     .07       0
Bank Sta=5017.9,5034.9
XS Rating Curve= 0 ,0
Exp/Cntr=0.3,0.1

Type RM Length L Ch R = 1 ,30756   ,450,450,450
BEGIN DESCRIPTION:
Bitter Creek Trib14 46.0
END DESCRIPTION:
XS GIS Cut Line= 3
      1398405.04      6829388.01      1398955.33      6829538.14
      1399155.03      6829487.99
#Sta/Elev= 30
  4429.6 2268.65  4481.4 2256.24  4521.1  2251.5  4600.6 2245.66  4616.1 2242.16
  4714.6 2236.94  4788.8 2227.32  4823.4 2228.39  4828.6 2232.05  4854.5 2237.61
  4875.3  2238.8  4902.8 2232.47  4947.8 2226.98  4977.1 2217.67  4988.5 2216.91
    4989 2216.41  5005.9 2216.91  5059.3 2225.31  5064.4 2223.45  5082.1 2226.47
  5100.4 2232.86  5105.6 2229.32  5123.4 2235.89  5141.6 2239.35  5146.7 2235.11
  5164.6 2234.78  5174.9 2236.58  5182.7 2242.15  5195.6 2246.07  5205.9 2246.43
#Mann= 3 ,-1 , 0
  4429.6     .07       0  4988.5     .07       0  5005.9     .07       0
Bank Sta=4988.5,5005.9
XS Rating Curve= 0 ,0
Exp/Cntr=0.3,0.1

Type RM Length L Ch R = 1 ,30306   ,495,495,495
BEGIN DESCRIPTION:
Bitter Creek Trib14 45.0
END DESCRIPTION:
XS GIS Cut Line= 3
      1398605.03        6829888.      1398824.71      6829917.85
      1399005.04      6830038.02
#Sta/Elev= 30
  4778.3 2239.67  4798.5 2238.79  4814.5 2236.08  4819.5 2236.44  4838.8 2230.95
  4848.9 2231.54  4879.2 2231.21    4887 2230.48    4892 2226.45  4909.5    2225
    4970 2217.72  5003.2  2217.8  5007.8  2215.7  5013.8 2216.11  5019.9  2214.1
  5020.4  2213.6  5037.9  2214.1  5043.9 2224.08  5058.9 2229.39  5064.9 2227.24
  5079.9 2230.55  5085.9 2229.15    5101 2231.17    5116 2232.09    5131 2235.09
    5137 2234.15  5144.6 2238.07  5152.1 2238.04  5167.1 2239.55  5216.7 2239.73
#Mann= 3 ,-1 , 0
  4778.3     .07       0  5019.9     .07       0  5037.9     .07       0
Bank Sta=5019.9,5037.9
XS Rating Curve= 0 ,0
Exp/Cntr=0.3,0.1

Type RM Length L Ch R = 1 ,29811   ,497,497,497
BEGIN DESCRIPTION:
Bitter Creek Trib14 44.0
END DESCRIPTION:
XS GIS Cut Line= 3
      1398404.95      6830237.98      1398655.16      6830353.06
      1398854.99        6830338.
#Sta/Elev= 30
  4724.6 2238.09  4756.4 2234.14  4761.9 2234.81  4779.3 2232.54  4784.8 2233.01
  4790.7  2231.6  4813.3 2229.24  4853.7 2226.21  4889.8 2221.25  4899.7 2220.91
  4911.8 2219.29  4928.2 2218.15  4944.8 2218.17  4966.8 2217.03  4979.6 2215.57
  4988.8  2212.8  4990.9 2210.63  4991.4 2210.13  5008.4 2210.13  5008.9 2210.63
  5009.9 2212.21    5040 2214.99    5070 2220.21  5090.1 2221.99  5110.2 2225.26
  5129.5 2232.22  5134.6 2231.42  5160.3 2232.11  5190.4 2237.21  5200.4 2237.39
#Mann= 3 ,-1 , 0
  4724.6     .07       0  4990.9     .07       0  5008.9     .07       0
Bank Sta=4990.9,5008.9
XS Rating Curve= 0 ,0
Exp/Cntr=0.3,0.1

Type RM Length L Ch R = 1 ,29314   ,489,489,489
BEGIN DESCRIPTION:
Bitter Creek Trib14 43.0
END DESCRIPTION:
XS GIS Cut Line= 3
      1398009.82      6830686.56      1398421.78       6830771.4
      1398604.99        6830688.
#Sta/Elev= 30
  4579.4 2236.73  4756.6 2234.01  4819.5 2234.23  4857.2 2231.95  4862.3 2232.44
    4891 2229.62  4901.2 2229.89  4907.5 2228.64  4921.6 2222.77  4931.8 2220.08
  4962.9 2209.14  4972.7 2205.54  4973.9 2203.68  4974.4 2203.18  4991.9 2203.68
  4993.1 2205.89  4999.1 2209.23  5004.5 2209.23  5020.2  2214.2  5025.6  2213.7
  5043.2 2215.96  5058.5 2215.57  5089.3 2218.99  5094.8 2218.05  5102.4 2218.46
  5112.4 2219.96  5117.9 2219.77  5124.4 2221.53  5169.5 2224.42  5201.3 2228.58
#Mann= 3 ,-1 , 0
  4579.4     .07       0  4973.9     .07       0  4991.9     .07       0
Bank Sta=4973.9,4991.9
XS Rating Curve= 0 ,0
Exp/Cntr=0.3,0.1

Type RM Length L Ch R = 1 ,28825   ,497,497,497
BEGIN DESCRIPTION:
Bitter Creek Trib14 42.0
END DESCRIPTION:
XS GIS Cut Line= 3
      1398505.03      6831287.96      1398648.92      6831140.55
      1398804.97      6830988.03
#Sta/Elev= 30
    4794 2228.18  4845.3 2228.41  4864.6  2228.5  4892.9 2226.76    4900 2227.34
    4907 2225.43  4914.2 2225.18  4921.2 2222.98  4928.3 2222.22  4935.3 2219.78
  4942.5 2218.97  4949.5 2215.17  4956.6 2212.89  4963.6 2207.93  4970.8 2206.55
  4975.9 2203.02  4976.4 2202.52  4993.9 2203.02  4998.6 2204.52  5020.3 2208.48
  5034.4  2209.5    5091 2211.11  5112.2 2212.92  5147.6 2218.99  5182.9  2223.2
    5190 2223.18    5197 2225.44  5204.2 2226.46  5211.2 2229.64  5218.2 2229.01
#Mann= 5 ,-1 , 0
    4794     .07       0  4845.3    .035       0  4975.9     .07       0
  4993.9    .035       0  4998.6     .07       0
Bank Sta=4975.9,4993.9
XS Rating Curve= 0 ,0
Exp/Cntr=0.3,0.1

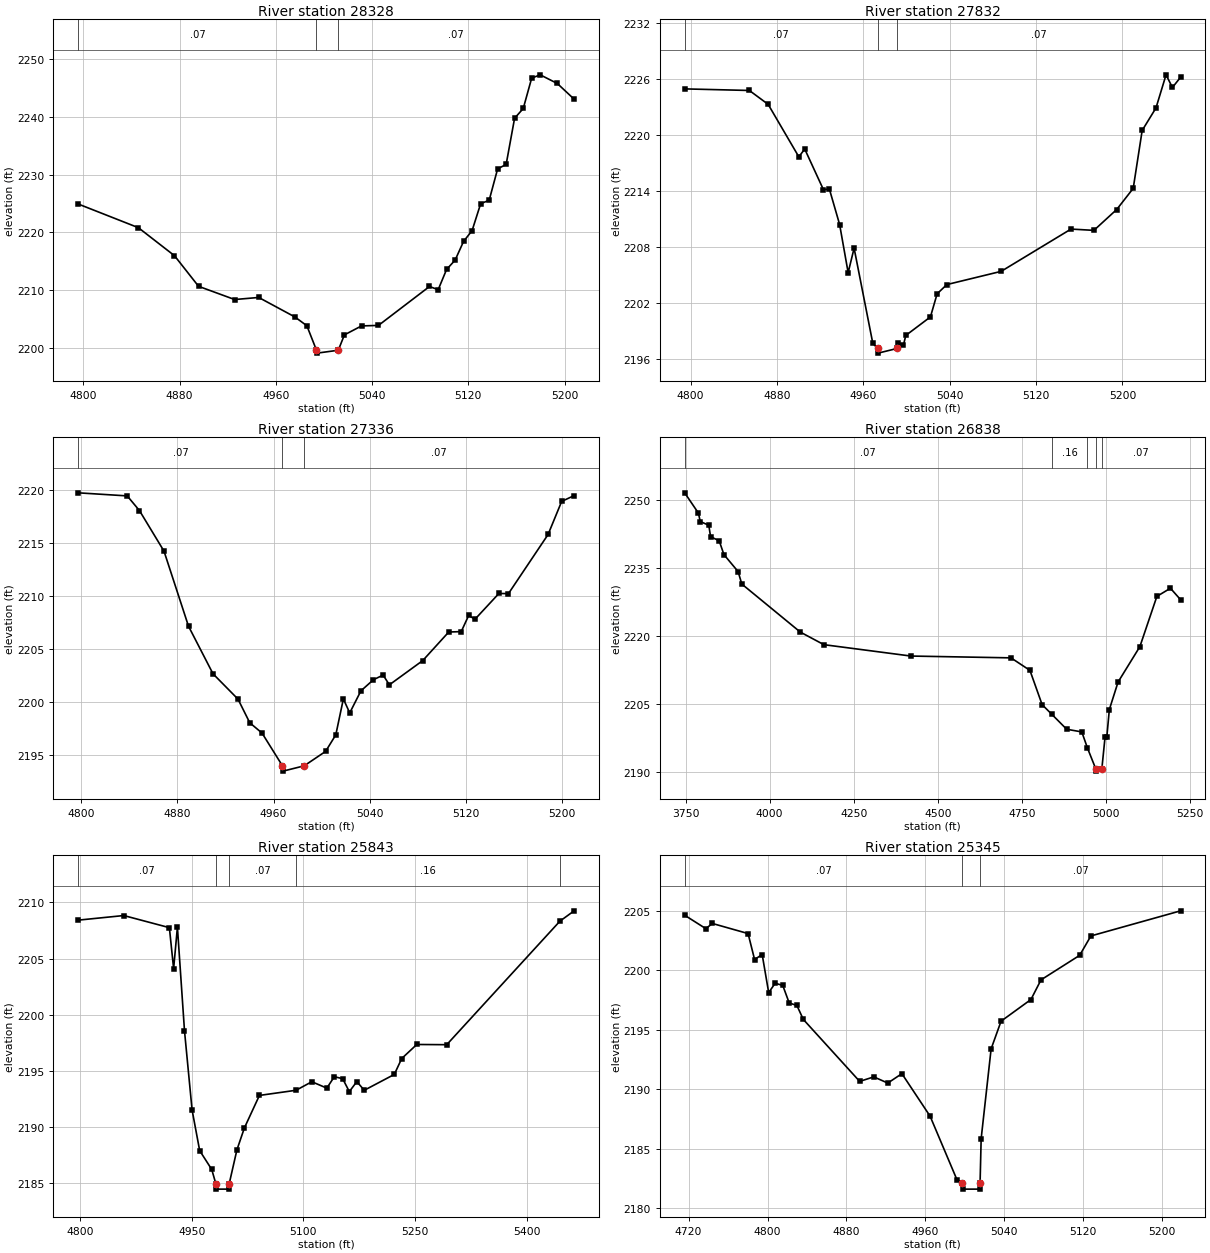
Type RM Length L Ch R = 1 ,28328   ,496,496,496
BEGIN DESCRIPTION:
Bitter Creek Trib14 41.0
END DESCRIPTION:
XS GIS Cut Line= 3
        1398605.        6831538.      1398809.19      6831539.73
      1398954.97      6831687.97
#Sta/Elev= 30
  4795.8 2224.93  4845.8 2220.83  4875.8 2215.98  4895.8 2210.68  4925.8 2208.39
  4945.8 2208.75  4975.8 2205.38  4985.8 2203.85  4993.8 2199.61  4994.3 2199.11
  5011.9 2199.61    5017 2202.27  5031.2 2203.82  5045.3 2203.91  5087.7 2210.65
  5094.9 2210.09  5101.9  2213.6    5109 2215.22    5116 2218.45  5123.1 2220.33
  5130.2 2224.98  5137.3 2225.59  5144.3 2231.01  5151.4 2231.79  5158.4 2239.78
  5165.6 2241.47  5172.6 2246.73  5179.7  2247.3  5193.9  2245.8  5207.9 2243.08
#Mann= 3 ,-1 , 0
  4795.8     .07       0  4993.8     .07       0  5011.9     .07       0
Bank Sta=4993.8,5011.9
XS Rating Curve= 0 ,0
Exp/Cntr=0.3,0.1

Type RM Length L Ch R = 1 ,27832   ,496,496,496
BEGIN DESCRIPTION:
Bitter Creek Trib14 40.0
END DESCRIPTION:
XS GIS Cut Line= 3
      1398504.97      6831887.99       1398691.1      6831974.84
      1398904.98      6831838.01
#Sta/Elev= 30
  4794.6 2224.97  4854.5  2224.8  4871.9 2223.31  4900.3 2217.68  4905.8 2218.51
  4923.1 2214.15  4928.6 2214.22  4938.1 2210.41    4946 2205.24  4951.5 2207.87
  4968.8 2197.67  4973.2  2197.1  4973.7  2196.6  4991.3  2197.1  4991.7 2197.74
  4997.2 2197.47  4999.4  2198.5  5022.2 2200.49  5028.4 2202.97  5037.4 2203.96
  5087.7 2205.38  5152.4 2209.92  5173.6 2209.78  5194.7 2212.02    5210 2214.29
  5218.3 2220.51  5231.1 2222.93  5240.4 2226.48  5246.3 2225.12  5253.9 2226.23
#Mann= 3 ,-1 , 0
  4794.6     .07       0  4973.2     .07       0  4991.3     .07       0
Bank Sta=4973.2,4991.3
XS Rating Curve= 0 ,0
Exp/Cntr=0.3,0.1

Type RM Length L Ch R = 1 ,27336   ,498,498,498
BEGIN DESCRIPTION:
Bitter Creek Trib14 39.0
END DESCRIPTION:
XS GIS Cut Line= 3
      1398704.96      6832438.01      1398903.68      6832398.55
      1399104.98      6832338.01
#Sta/Elev= 30
  4797.4 2219.74  4838.2 2219.45  4848.4 2218.06  4868.8 2214.24  4889.2 2207.16
  4909.6 2202.67  4930.4 2200.28  4940.2 2198.05  4950.4 2197.08  4967.4 2193.99
  4967.9 2193.49  4985.5 2193.99  5003.3 2195.35  5011.8 2196.91  5018.1  2200.3
  5023.4 2198.98  5032.7 2201.06  5043.1 2202.11  5051.2 2202.55  5056.4 2201.63
  5084.2 2203.92  5105.8 2206.61  5116.2 2206.65  5122.4 2208.17  5127.7 2207.82
  5147.6 2210.25  5155.5 2210.23  5188.5 2215.81  5199.8 2218.93  5210.2 2219.48
#Mann= 3 ,-1 , 0
  4797.4     .07       0  4967.4     .07       0  4985.5     .07       0
Bank Sta=4967.4,4985.5
XS Rating Curve= 0 ,0
Exp/Cntr=0.3,0.1

Type RM Length L Ch R = 1 ,26838   ,995,995,995
BEGIN DESCRIPTION:
Bitter Creek Trib14 38.0
END DESCRIPTION:
XS GIS Cut Line= 3
      1398005.04      6833187.99      1399185.21      6832767.91
      1399404.98        6832738.
#Sta/Elev= 30
  3747.3 2251.58  3788.2  2247.1  3793.5 2245.25    3819 2244.43  3824.3  2241.9
  3849.9    2241    3864 2237.95  3906.2  2234.2  3917.1 2231.46  4091.2 2220.85
  4161.2 2218.08  4419.8 2215.57  4717.5 2215.17  4773.8 2212.41    4810 2204.85
  4838.5 2202.74    4883 2199.42    4928 2198.83  4944.7  2195.3  4969.5 2190.68
    4970 2190.18  4987.6 2190.68  4997.2 2197.75  5002.4 2197.75  5009.9 2203.77
  5035.8 2209.83  5100.7 2217.65  5151.2 2228.73  5191.5 2230.53  5221.8 2227.99
#Mann= 5 ,-1 , 0
  3747.3     .07       0  4838.5     .16       0  4944.7     .07       0
  4969.5     .07       0  4987.6     .07       0
Bank Sta=4969.5,4987.6
XS Rating Curve= 0 ,0
Exp/Cntr=0.3,0.1

Type RM Length L Ch R = 1 ,25843   ,498,498,498
BEGIN DESCRIPTION:
Bitter Creek Trib14 37.0
END DESCRIPTION:
XS GIS Cut Line= 3
      1399304.98        6833638.      1399503.43       6833598.7
        1399555.      6833137.98
#Sta/Elev= 30
  4797.7 2208.42  4858.9 2208.83  4920.1 2207.75  4925.8  2204.1  4930.9 2207.79
  4940.4 2198.56  4950.6  2191.5  4960.8 2187.88    4977  2186.2  4982.4 2184.95
  4982.9 2184.45    5000 2184.45  5000.5 2184.95  5010.8 2187.95  5020.8  2189.9
    5041  2192.8  5090.2 2193.26  5111.4 2194.02  5131.5 2193.45  5141.6 2194.47
  5152.8 2194.29  5161.7 2193.14  5171.8 2194.03  5181.8 2193.26  5222.1 2194.67
  5232.1 2196.09  5252.3 2197.34  5292.5 2197.32  5444.5 2208.33  5463.6 2209.25
#Mann= 5 ,-1 , 0
  4797.7     .07       0  4982.4     .07       0  5000.5     .07       0
  5090.2     .16       0  5444.5     .07       0
Bank Sta=4982.4,5000.5
XS Rating Curve= 0 ,0
Exp/Cntr=0.3,0.1

Type RM Length L Ch R = 1 ,25345   ,488,488,488
BEGIN DESCRIPTION:
Bitter Creek Trib14 36.0
END DESCRIPTION:
XS GIS Cut Line= 3
      1399604.96      6833738.03      1399821.67      6833554.47
        1399855.      6833338.02
#Sta/Elev= 30
    4716 2204.62  4737.5 2203.49    4744 2203.93  4780.3 2203.08  4786.9  2200.9
  4794.6 2201.32  4801.2 2198.12  4807.8 2198.91  4815.5 2198.72    4822 2197.25
  4829.8 2197.04  4836.3 2195.87  4893.5 2190.66  4907.8 2191.04    4922 2190.52
  4936.3 2191.31  4964.9 2187.74  4992.3 2182.37  4997.4 2182.11  4997.9 2181.61
  5015.1 2181.61  5015.6 2182.11  5016.7 2185.85  5026.8 2193.39  5036.9 2195.72
  5067.2 2197.54  5077.4 2199.19  5116.6 2201.25    5128 2202.88    5219 2204.99
#Mann= 3 ,-1 , 0
    4716     .07       0  4997.4     .07       0  5015.6     .07       0
Bank Sta=4997.4,5015.6
XS Rating Curve= 0 ,0
Exp/Cntr=0.3,0.1

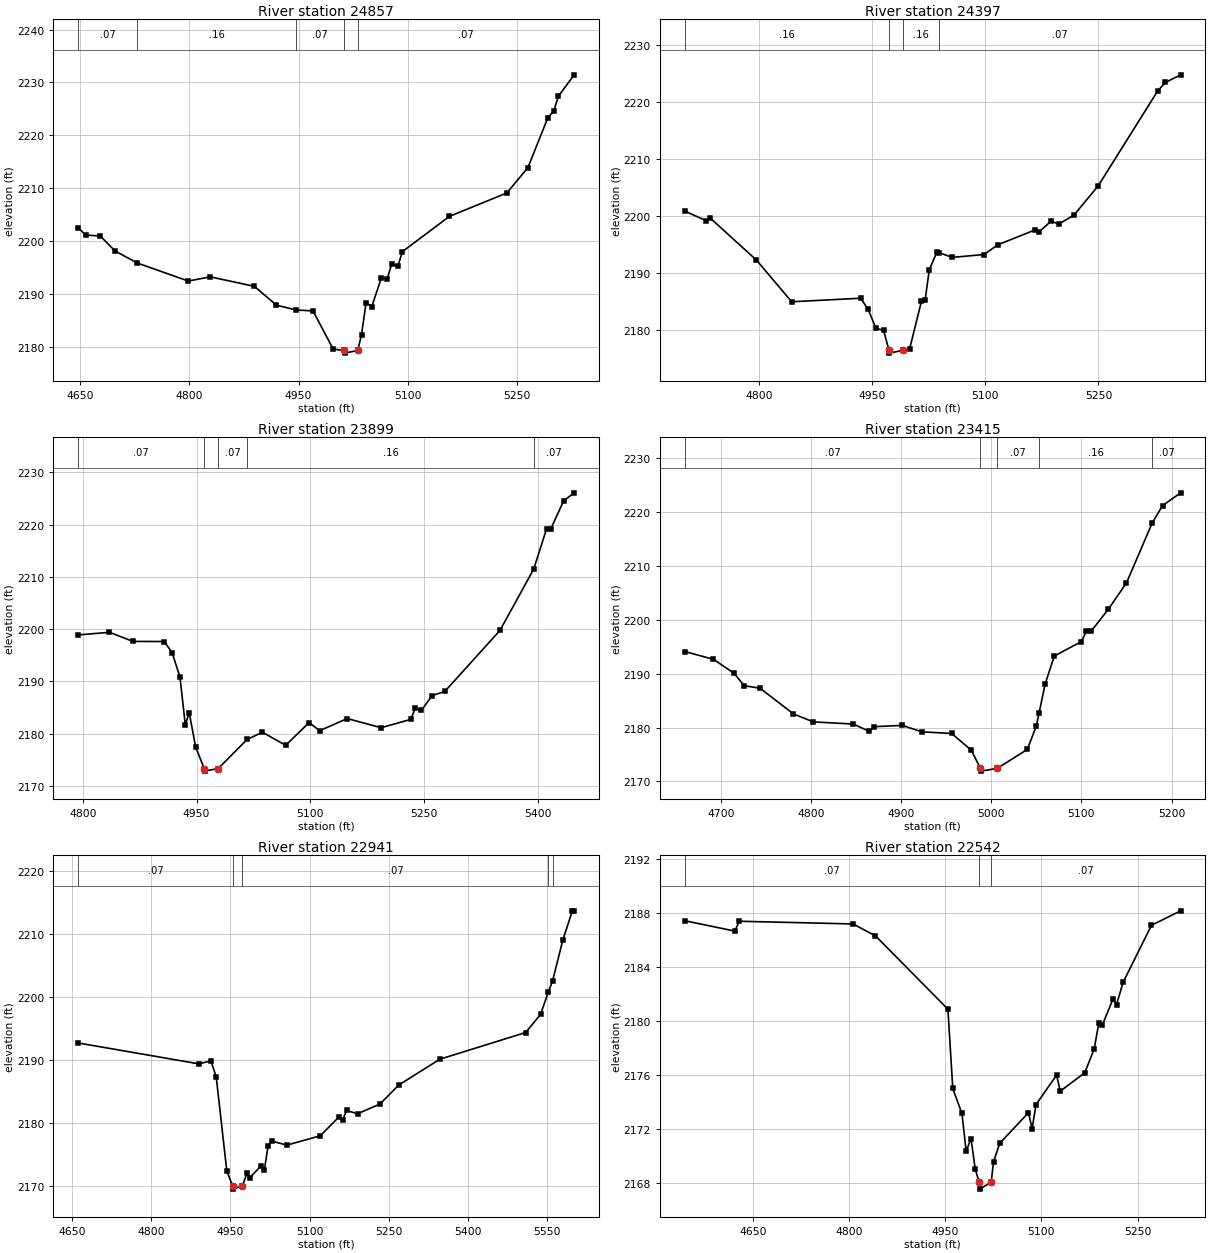
Type RM Length L Ch R = 1 ,24857   ,460,460,460
BEGIN DESCRIPTION:
Bitter Creek Trib14 35.0
END DESCRIPTION:
XS GIS Cut Line= 3
      1399704.96        6833988.      1400054.89      6833948.05
      1400254.98      6833688.02
#Sta/Elev= 30
  4647.8 2202.55  4657.9 2201.14    4678 2200.97  4698.2 2198.15  4728.8 2195.86
  4798.8 2192.45    4829 2193.24  4889.4 2191.45  4919.6  2187.9  4946.8 2186.97
  4969.9  2186.8  4997.5 2179.59  5012.6 2179.32  5013.1 2178.82  5031.2 2179.32
  5036.4  2182.3  5042.7 2188.37  5050.5 2187.62  5063.5 2192.98  5071.7 2192.91
    5078 2195.75  5086.2 2195.23  5092.5 2198.01  5156.9 2204.67  5235.7  2209.1
  5264.7  2213.9  5291.9 2223.29  5300.1 2224.61  5306.4 2227.37  5328.1 2231.44
#Mann= 5 ,-1 , 0
  4647.8     .07       0  4728.8     .16       0  4946.8     .07       0
  5012.6     .07       0  5031.2     .07       0
Bank Sta=5012.6,5031.2
XS Rating Curve= 0 ,0
Exp/Cntr=0.3,0.1

Type RM Length L Ch R = 1 ,24397   ,498,498,498
BEGIN DESCRIPTION:
Bitter Creek Trib14 34.0
END DESCRIPTION:
XS GIS Cut Line= 3
      1399804.99        6834438.      1400099.25      6834390.33
      1400454.97        6834438.
#Sta/Elev= 30
  4701.9 2200.92  4730.2 2199.23  4735.3 2199.73  4796.9 2192.32  4843.7    2185
  4934.9 2185.62    4945 2183.66  4955.2 2180.36  4965.3    2180  4972.6 2176.49
  4973.1 2175.99  4991.2 2176.49    5000 2176.78  5015.5 2185.05  5020.5 2185.38
    5026 2190.64  5036.1 2193.73  5038.9 2193.63  5056.2 2192.78  5098.5 2193.29
  5116.8    2195  5166.4 2197.62  5171.5  2197.3  5187.4 2199.14  5197.5 2198.63
  5217.7 2200.21  5249.5 2205.29  5328.7 2222.02  5338.7 2223.47  5358.9 2224.81
#Mann= 4 ,-1 , 0
  4701.9     .16       0  4972.6     .07       0  4991.2     .16       0
  5038.9     .07       0
Bank Sta=4972.6,4991.2
XS Rating Curve= 0 ,0
Exp/Cntr=0.3,0.1

Type RM Length L Ch R = 1 ,23899   ,484,484,484
BEGIN DESCRIPTION:
Bitter Creek Trib14 33.0
END DESCRIPTION:
XS GIS Cut Line= 3
      1399855.02        6834788.      1400054.66      6834838.37
      1400455.02      6834637.99
#Sta/Elev= 30
  4794.1 2198.89  4835.3 2199.39  4866.3 2197.65  4907.5 2197.63  4917.8 2195.51
  4928.2 2190.84  4935.2 2181.71  4940.4 2184.04  4948.8  2177.5  4960.1 2173.35
  4960.6 2172.85  4978.7 2173.35  5016.6  2178.9  5036.9 2180.28  5067.5 2177.79
  5098.4 2182.13  5112.2 2180.58  5148.7  2182.9  5193.4 2181.15  5232.5 2182.75
  5238.1 2184.83  5246.4 2184.47  5260.5 2187.29  5277.2 2188.08  5349.9 2199.74
  5394.4 2211.48  5411.4  2219.2  5416.9 2219.15  5433.7 2224.49  5447.7 2226.06
#Mann= 5 ,-1 , 0
  4794.1     .07       0  4960.1     .07       0  4978.7     .07       0
  5016.6     .16       0  5394.4     .07       0
Bank Sta=4960.1,4978.7
XS Rating Curve= 0 ,0
Exp/Cntr=0.3,0.1

Type RM Length L Ch R = 1 ,23415   ,474,474,474
BEGIN DESCRIPTION:
Bitter Creek Trib14 32.0
END DESCRIPTION:
XS GIS Cut Line= 3
        1400155.        6835038.      1400465.11      6834897.85
        1400455.        6834688.
#Sta/Elev= 30
  4659.7 2194.12  4691.6 2192.68  4714.6 2190.07  4725.7 2187.78  4743.3 2187.31
  4780.4 2182.54  4802.4 2181.06  4846.8 2180.66  4864.4 2179.32  4869.9 2180.17
  4901.1 2180.41  4923.1 2179.21    4956 2178.91  4977.9 2175.79  4987.9 2172.42
  4988.4 2171.92  5006.5 2172.42  5039.9 2175.94  5049.9 2180.24  5052.9 2182.62
  5059.9 2188.18  5069.9 2193.27    5100 2195.98  5105.6 2197.94  5110.6 2197.85
    5130    2202    5150 2206.86  5178.6    2218  5190.1 2221.21  5210.1 2223.58
#Mann= 5 ,-1 , 0
  4659.7     .07       0  4987.9     .07       0  5006.5     .07       0
  5052.9     .16       0  5178.6     .07       0
Bank Sta=4987.9,5006.5
XS Rating Curve= 0 ,0
Exp/Cntr=0.3,0.1

Type RM Length L Ch R = 1 ,22941   ,399,399,399
BEGIN DESCRIPTION:
Bitter Creek Trib14 31.0
END DESCRIPTION:
XS GIS Cut Line= 3
      1400205.03        6835238.      1400541.63      6835274.68
        1400955.        6834838.
#Sta/Elev= 30
  4661.4 2192.76  4889.9 2189.45  4912.9 2189.91  4922.9  2187.4    4943 2172.46
  4953.9 2170.07  4954.4 2169.57  4972.5 2170.07  4981.4 2172.11  4986.4 2171.37
  5007.2  2173.2  5014.1  2172.6  5021.4 2176.47  5028.3  2177.2  5056.6 2176.55
  5120.1 2178.03  5155.7 2181.04  5162.6 2180.53  5169.9 2182.05  5190.9 2181.53
  5233.4 2183.08    5269 2186.09  5346.6 2190.18  5509.3 2194.42  5537.6 2197.29
  5552.5 2200.89  5560.4 2202.62  5580.1 2209.17  5597.9 2213.73  5601.3 2213.73
#Mann= 5 ,-1 , 0
  4661.4     .07       0  4953.9     .07       0  4972.5     .07       0
  5552.5     .16       0  5560.4     .07       0
Bank Sta=4953.9,4972.5
XS Rating Curve= 0 ,0
Exp/Cntr=0.3,0.1

Type RM Length L Ch R = 1 ,22542   ,565,565,565
BEGIN DESCRIPTION:
Bitter Creek Trib14 30.0
END DESCRIPTION:
XS GIS Cut Line= 3
      1400505.03      6835787.98      1400849.97      6835488.81
      1400999.36        6835209.
#Sta/Elev= 30
  4543.4 2187.42  4621.7 2186.65  4628.4 2187.38    4806 2187.18  4841.1  2186.3
  4954.1 2180.88  4961.7 2175.02    4976 2173.17  4982.6 2170.38  4990.2 2171.32
  4996.8 2169.04    5003 2168.08  5003.5 2167.58  5021.6 2168.08  5025.3  2169.6
  5034.9 2170.96  5079.8 2173.23  5085.5 2172.05  5091.6 2173.83  5123.7 2176.01
  5129.4 2174.82  5167.6 2176.18  5182.3 2177.93  5189.6 2179.86  5195.2 2179.72
  5211.5 2181.61  5217.2 2181.22  5227.6 2182.88  5271.7 2187.08  5317.2 2188.15
#Mann= 3 ,-1 , 0
  4543.4     .07       0    5003     .07       0  5021.6     .07       0
Bank Sta=5003,5021.6
XS Rating Curve= 0 ,0
Exp/Cntr=0.3,0.1

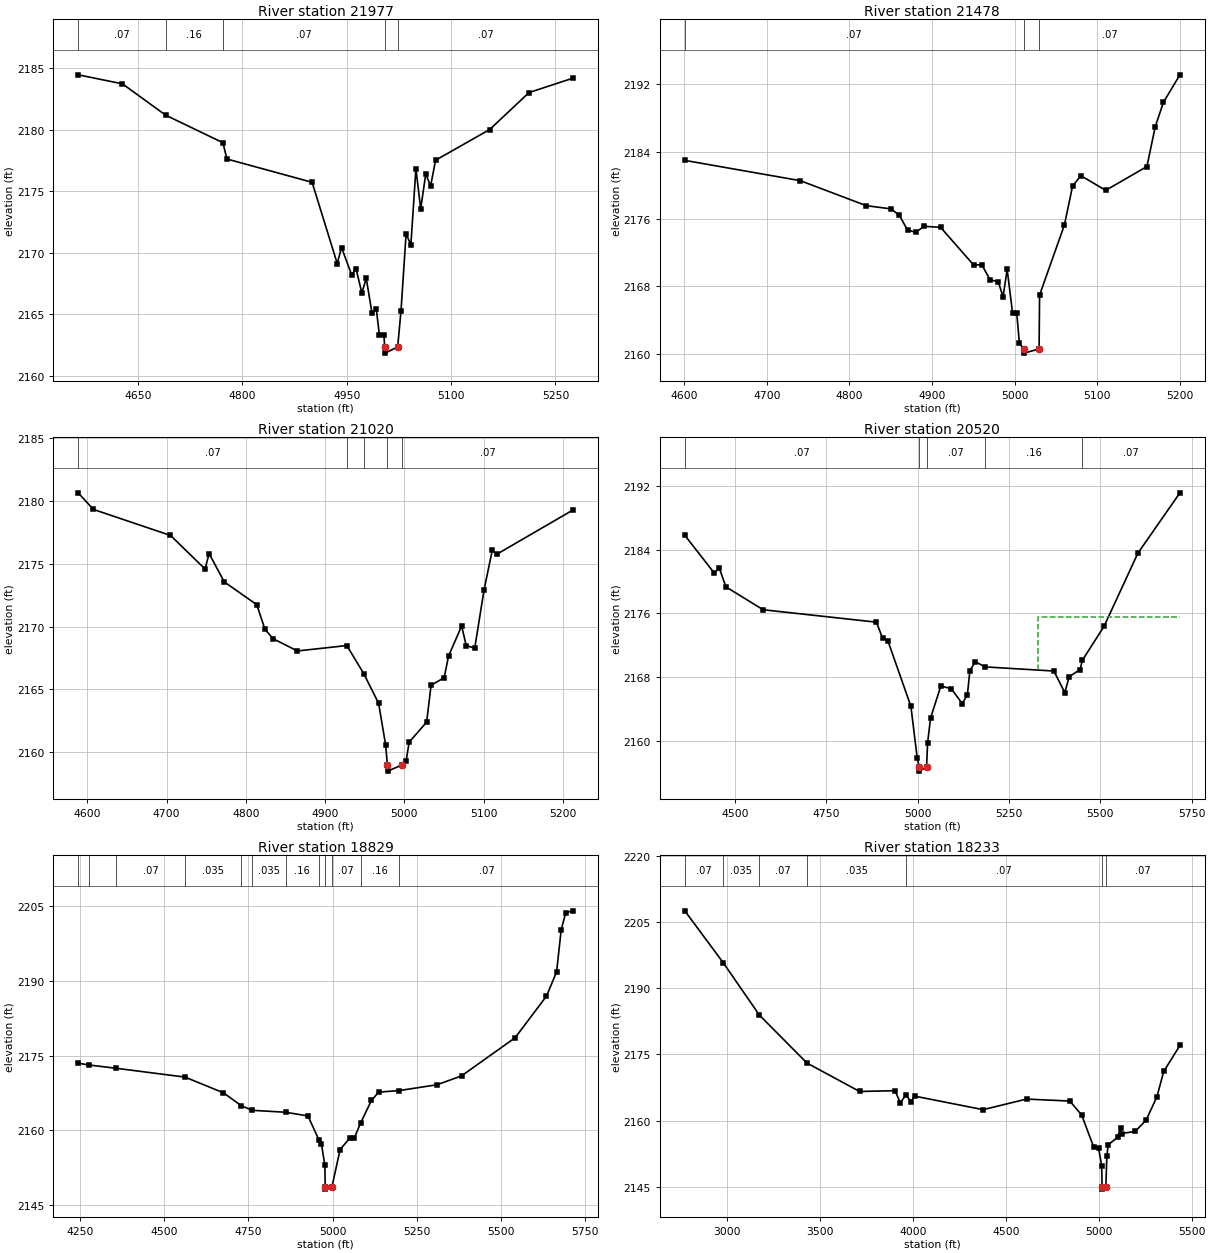
Type RM Length L Ch R = 1 ,21977   ,499,499,499
BEGIN DESCRIPTION:
Bitter Creek Trib14 29.0
END DESCRIPTION:
XS GIS Cut Line= 3
      1400905.02      6835937.98      1401255.12      6835677.95
      1401454.97      6835488.03
#Sta/Elev= 30
  4563.9 2184.44  4627.5 2183.71  4689.6 2181.17    4772 2178.93  4777.7 2177.61
  4900.2 2175.72  4936.3 2169.13  4942.5 2170.43  4957.1  2168.2  4963.3 2168.72
  4971.7 2166.74    4978 2167.94  4986.3  2165.1  4992.6  2165.4  4996.8 2163.37
  5003.4 2163.37  5004.5 2162.36    5005 2161.86  5023.2 2162.36    5028  2165.3
  5035.3 2171.53  5042.2 2170.66  5049.4 2176.83  5056.3 2173.57  5063.6 2176.41
  5070.5 2175.41  5077.7 2177.51  5155.4    2180    5212    2183  5275.7 2184.18
#Mann= 5 ,-1 , 0
  4563.9     .07       0  4689.6     .16       0    4772     .07       0
  5004.5     .07       0  5023.2     .07       0
Bank Sta=5004.5,5023.2
XS Rating Curve= 0 ,0
Exp/Cntr=0.3,0.1

Type RM Length L Ch R = 1 ,21478   ,458,458,458
BEGIN DESCRIPTION:
Bitter Creek Trib14 28.0
END DESCRIPTION:
XS GIS Cut Line= 3
      1401055.02        6836038.      1401454.59      6836043.17
      1401655.02        6836038.
#Sta/Elev= 30
  4600.4 2182.97  4740.4 2180.56  4820.4 2177.59  4850.4 2177.21  4860.4 2176.45
  4870.4 2174.69  4880.4 2174.43  4890.4 2175.14  4910.4 2175.02  4950.4 2170.55
  4960.4 2170.57  4970.4 2168.79  4980.4 2168.55  4986.1 2166.75  4991.1 2170.02
  4997.7 2164.82  5002.7 2164.82    5006 2161.24  5011.1 2160.58  5011.6 2160.08
  5029.8 2160.58  5030.4 2166.98  5060.4 2175.27  5070.4 2179.92  5080.4 2181.16
  5110.5 2179.41  5160.5 2182.24  5170.5 2186.94  5180.5 2189.87  5200.5 2193.13
#Mann= 3 ,-1 , 0
  4600.4     .07       0  5011.1     .07       0  5029.8     .07       0
Bank Sta=5011.1,5029.8
XS Rating Curve= 0 ,0
Exp/Cntr=0.3,0.1

Type RM Length L Ch R = 1 ,21020   ,500,500,500
BEGIN DESCRIPTION:
Bitter Creek Trib14 27.0
END DESCRIPTION:
XS GIS Cut Line= 3
      1401254.96      6836337.99      1401656.65      6836427.32
      1401754.98      6836238.03
#Sta/Elev= 30
  4588.5 2180.64  4607.7 2179.32    4705 2177.25  4748.6 2174.58  4753.7 2175.81
  4772.9 2173.55  4813.9 2171.74  4824.2 2169.78  4834.4 2169.04  4865.1 2168.06
  4927.5 2168.49  4948.9 2166.25  4967.6  2163.9  4976.4 2160.61  4978.7    2159
  4979.2  2158.5  4997.4    2159  5002.4 2159.33  5006.1  2160.8  5028.2  2162.4
  5033.8 2165.33  5050.3 2165.93  5055.9 2167.66  5072.4 2170.05  5078.1 2168.49
  5088.9 2168.28  5100.6  2172.9    5111 2176.06  5116.6 2175.75  5213.3 2179.29
#Mann= 5 ,-1 , 0
  4588.5     .07       0  4927.5     .16       0  4948.9     .07       0
  4978.7     .07       0  4997.4     .07       0
Bank Sta=4978.7,4997.4
XS Rating Curve= 0 ,0
Exp/Cntr=0.3,0.1

Type RM Length L Ch R = 1 ,20520   ,1691,1691,1691
BEGIN DESCRIPTION:
Bitter Creek Trib14 26.0
END DESCRIPTION:
XS GIS Cut Line= 3
      1401154.98      6837088.01      1401762.82      6836894.19
        1402355.        6836488.
#Sta/Elev= 30
    4362 2185.79  4442.5 2181.07  4456.5 2181.67  4474.7 2179.32  4576.6 2176.45
  4886.8 2174.89  4903.9 2172.86  4918.3 2172.55  4981.3 2164.33  4998.5 2157.85
  5004.3  2156.7  5004.8  2156.2  5024.2  2156.7  5026.9  2159.7  5035.2 2162.87
  5063.3 2166.88    5092 2166.54  5121.8 2164.68    5136 2165.77  5142.8 2168.82
  5157.7 2169.93  5184.1 2169.28  5372.9 2168.76  5402.7 2166.06  5414.9 2168.04
  5444.7 2168.95  5450.7  2170.1  5510.3 2174.37    5603 2183.55  5718.1 2191.12
#Mann= 5 ,-1 , 0
    4362     .07       0  5004.3     .07       0  5024.2     .07       0
  5184.1     .16       0  5450.7     .07       0
#XS Ineff= 2 , 0
                         5328.93         2175.58
Permanent Ineff=
       F       F
Bank Sta=5004.3,5024.2
XS Rating Curve= 0 ,0
Exp/Cntr=0.3,0.1

Type RM Length L Ch R = 1 ,18829   ,596,596,596
BEGIN DESCRIPTION:
Bitter Creek Trib14 25.0
END DESCRIPTION:
XS GIS Cut Line= 3
      1401855.02        6837338.      1402607.73      6837281.84
      1403005.02      6836687.98
#Sta/Elev= 30
  4245.2 2173.48  4278.5 2173.11  4357.9 2172.46  4562.1 2170.69  4676.4 2167.53
  4728.5 2164.98  4761.1 2164.02  4860.5 2163.63  4927.1 2162.89    4960 2158.01
  4967.2 2157.17  4977.2 2153.04  4978.3 2148.69  4978.8 2148.19  4998.4 2148.69
  5022.4 2156.14  5052.4 2158.54  5064.8 2158.47    5083 2161.43  5115.5 2166.01
    5137 2167.67  5198.6 2167.99  5310.6 2169.16  5382.7 2170.93  5541.8 2178.59
  5634.9 2186.95  5664.9 2191.82  5678.4 2200.22    5692 2203.74  5714.5 2204.08
#Mann= 12 ,-1 , 0
  4245.2     .07       0  4278.5    .035       0  4357.9     .07       0
  4562.1    .035       0  4728.5     .07       0  4761.1    .035       0
  4860.5     .16       0    4960     .07       0  4978.3     .07       0
  4998.4     .07       0    5083     .16       0  5198.6     .07       0
Bank Sta=4978.3,4998.4
XS Rating Curve= 0 ,0
Exp/Cntr=0.3,0.1

Type RM Length L Ch R = 1 ,18233   ,1739,1739,1739
BEGIN DESCRIPTION:
Bitter Creek Trib14 24.0
END DESCRIPTION:
XS GIS Cut Line= 3
      1401304.97      6839288.03      1402928.18      6837761.71
      1403155.02      6837387.97
#Sta/Elev= 30
  2771.9 2207.51  2979.3 2195.73  3173.5 2183.89  3429.5 2173.03  3712.9 2166.59
  3903.8 2166.77  3932.2    2164  3962.3 2165.84  3988.8 2164.29  4009.8 2165.53
  4377.9 2162.47  4611.3 2164.87  4844.6 2164.42  4908.5 2161.24    4972 2154.11
  4999.1 2153.79    5016 2149.78  5018.1 2144.97  5018.6 2144.47  5038.3 2144.97
  5043.7 2151.93  5051.1 2154.52  5101.8  2156.2  5117.3  2158.4  5123.2 2157.05
  5196.8 2157.56    5255 2160.09  5313.1 2165.36  5349.9 2171.12  5437.2 2177.02
#Mann= 7 ,-1 , 0
  2771.9     .07       0  2979.3    .035       0  3173.5     .07       0
  3429.5    .035       0  3962.3     .07       0  5018.1     .07       0
  5038.3     .07       0
Bank Sta=5018.1,5038.3
XS Rating Curve= 0 ,0
Exp/Cntr=0.3,0.1