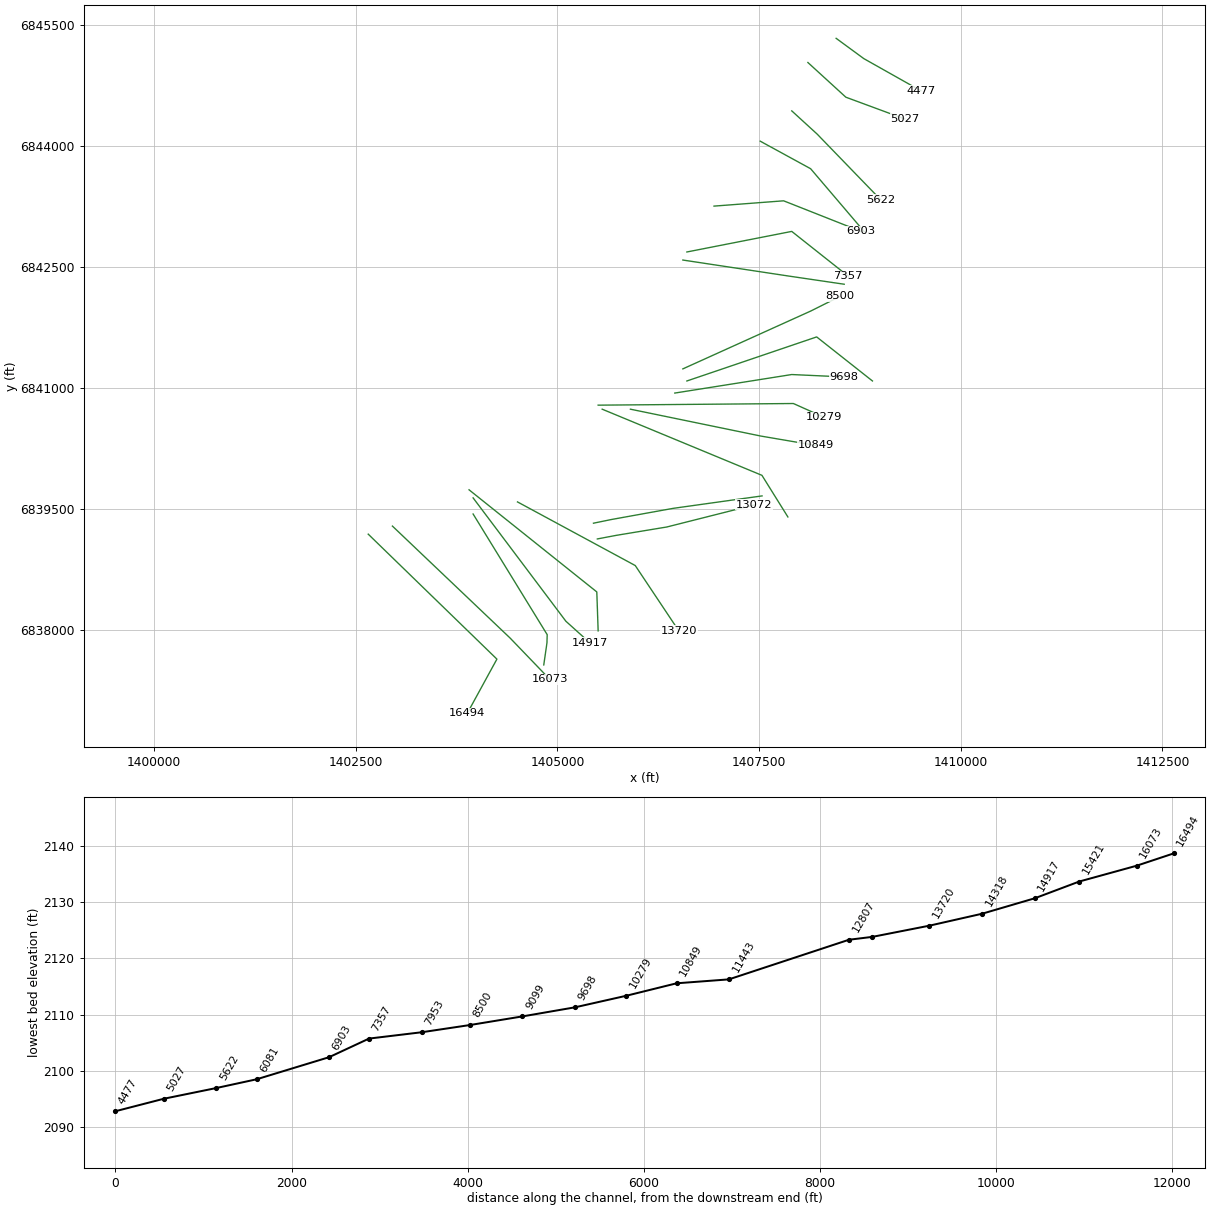
HEC-RAS study Bitter Creek Trib14.prj: Bitter Creek Trib14 Base Level Engineering

--- Bitter Creek Trib14.g01 (geometry) --- (continued)

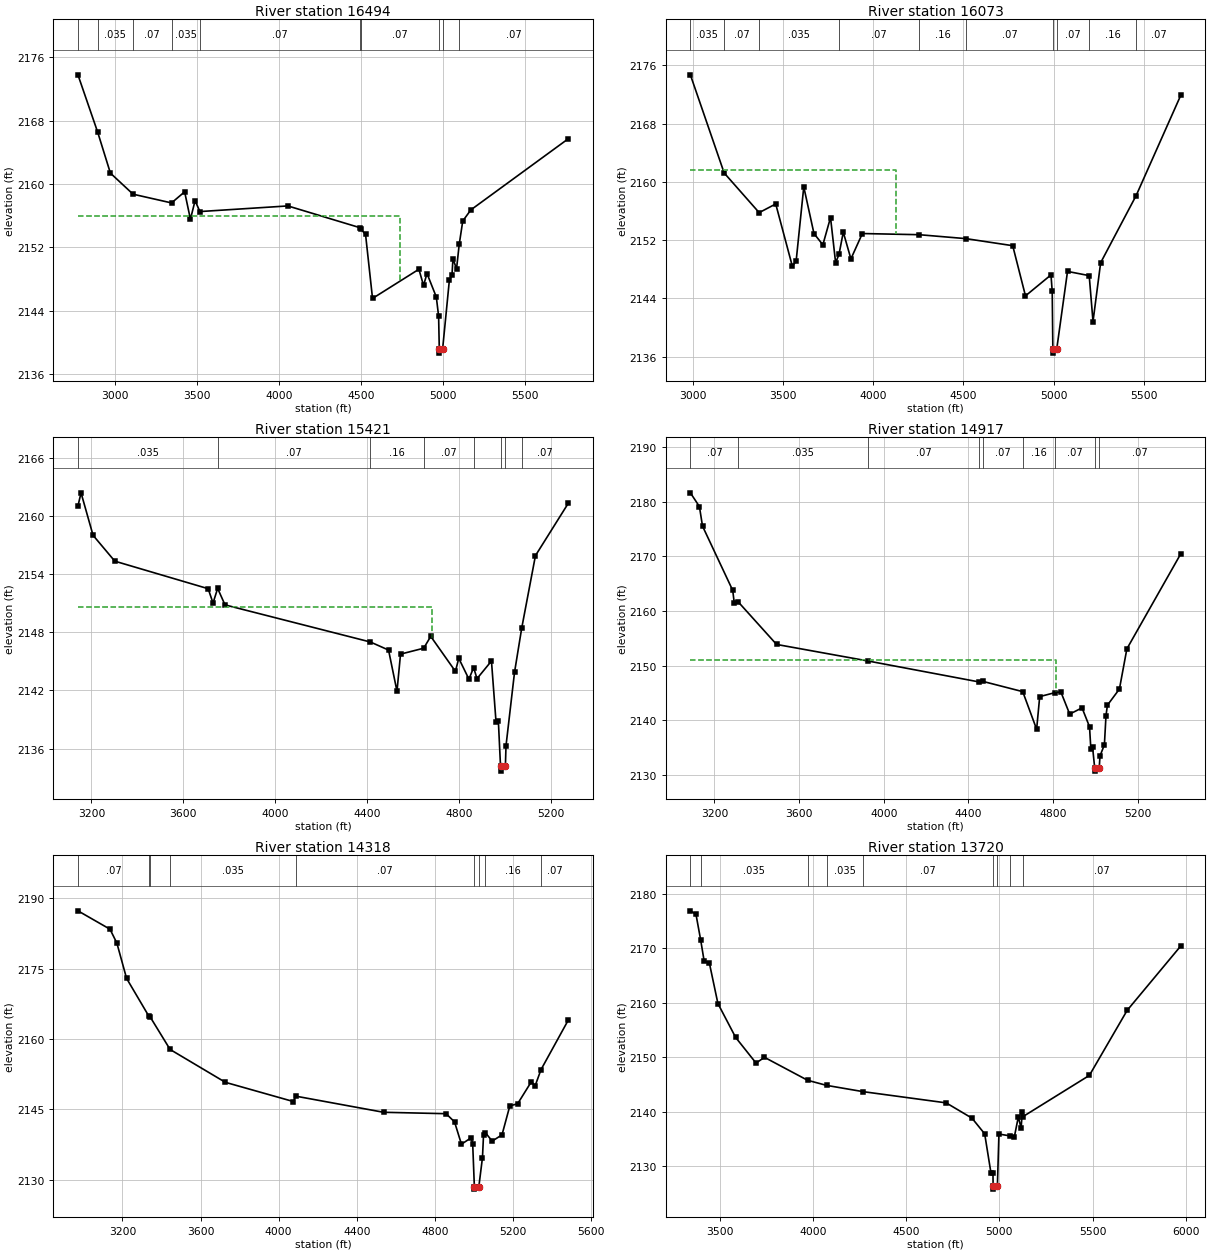
Type RM Length L Ch R = 1 ,16494   ,421,421,421
BEGIN DESCRIPTION:
Bitter Creek Trib14 23.0
END DESCRIPTION:
XS GIS Cut Line= 3
      1402655.03      6839187.97      1404250.03      6837637.94
      1403882.28      6836964.96
#Sta/Elev= 30
  2775.9 2173.78  2896.8 2166.51  2973.8 2161.38    3112 2158.72  3346.5 2157.62
  3426.5 2159.02  3461.8 2155.56  3490.1  2157.9  3519.7 2156.53  4055.9 2157.24
  4494.8  2154.5  4501.1 2154.31  4529.7 2153.64  4572.2 2145.57  4854.9 2149.25
  4883.2 2147.22  4904.5 2148.71  4961.1 2145.75  4975.2 2143.34  4979.3 2139.17
  4979.8 2138.67  4999.5 2139.17  5040.8 2147.88  5056.9 2148.56  5062.6 2150.59
  5084.4 2149.29  5100.8 2152.39  5122.4 2155.34  5171.7 2156.74  5766.9 2165.73
#Mann= 10 ,-1 , 0
  2775.9     .07       0  2896.8    .035       0    3112     .07       0
  3346.5    .035       0  3519.7     .07       0  4494.8     .16       0
  4501.1     .07       0  4979.3     .07       0  4999.5     .07       0
  5100.8     .07       0
#XS Ineff= 2 , 0
         4742.13 2155.91
Permanent Ineff=
       F       F
Bank Sta=4979.3,4999.5
XS Rating Curve= 0 ,0
Exp/Cntr=0.3,0.1

Type RM Length L Ch R = 1 ,16073   ,652,652,652
BEGIN DESCRIPTION:
Bitter Creek Trib14 22.0
END DESCRIPTION:
XS GIS Cut Line= 3
      1402955.01      6839287.99      1404415.19      6837897.68
      1404905.01      6837387.99
#Sta/Elev= 30
  2983.8 2174.69  3171.3 2161.22  3365.6 2155.77  3457.6 2156.96  3549.8 2148.42
  3570.9 2149.11  3613.3 2159.31  3669.9  2152.9  3719.3 2151.35  3761.8  2155.1
  3790.1 2148.89    3809 2150.05  3832.6 2153.09    3875 2149.42  3938.5  2152.9
  4253.6 2152.74  4513.2  2152.2  4773.3 2151.23  4844.1 2144.34  4985.7 2147.22
  4992.6 2144.95  4996.1 2136.98  4996.6 2136.48  5017.3 2136.98  5077.5  2147.7
  5197.9 2147.12    5219 2140.82  5261.4 2148.89  5458.6 2158.12  5706.9 2171.92
#Mann= 10 ,-1 , 0
  2983.8    .035       0  3171.3     .07       0  3365.6    .035       0
    3809     .07       0  4253.6     .16       0  4513.2     .07       0
  4996.1     .07       0  5017.3     .07       0  5197.9     .16       0
  5458.6     .07       0
#XS Ineff= 2 , 0
         4123.86 2161.69
Permanent Ineff=
       F       F
Bank Sta=4996.1,5017.3
XS Rating Curve= 0 ,0
Exp/Cntr=0.3,0.1

Type RM Length L Ch R = 1 ,15421   ,504,504,504
BEGIN DESCRIPTION:
Bitter Creek Trib14 21.0
END DESCRIPTION:
XS GIS Cut Line= 4
      1403955.03      6839437.96      1404873.39      6837941.33
      1404870.34       6837838.8      1404830.94      6837565.83
#Sta/Elev= 30
  3141.5 2161.02    3155 2162.38  3207.2    2158  3301.9 2155.33    3708 2152.49
  3729.3 2151.01  3749.4 2152.52  3781.4 2150.82  4414.1 2146.99    4493 2146.16
  4529.7 2141.91  4545.1 2145.74  4645.9 2146.35  4676.6 2147.57    4784 2143.96
  4798.5 2145.31  4842.7 2143.16  4863.2 2144.35  4877.9 2143.21  4940.8 2145.03
  4960.8  2138.7  4970.8 2138.86  4980.2 2134.17  4980.7 2133.67  5001.4 2134.17
  5004.1 2136.29  5041.2 2143.87  5072.4 2148.42  5132.2  2155.9  5275.8 2161.33
#Mann= 8 ,-1 , 0
  3141.5    .035       0  3749.4     .07       0  4414.1     .16       0
  4645.9     .07       0  4863.2     .16       0  4980.2     .07       0
  5001.4     .16       0  5072.4     .07       0
#XS Ineff= 2 , 0
         4682.74  2150.6
Permanent Ineff=
       F       F
Bank Sta=4980.2,5001.4
XS Rating Curve= 0 ,0
Exp/Cntr=0.3,0.1

Type RM Length L Ch R = 1 ,14917   ,599,599,599
BEGIN DESCRIPTION:
Bitter Creek Trib14 20.0
END DESCRIPTION:
XS GIS Cut Line= 3
      1403955.01      6839637.99      1405104.91      6838108.04
        1405405.        6837838.
#Sta/Elev= 30
  3086.1 2181.64  3128.8 2179.13  3143.4 2175.55  3286.2 2163.78  3293.3 2161.52
  3312.5 2161.66  3493.3 2153.89  3923.9 2150.87  4449.6 2147.03  4466.6 2147.14
  4656.4 2145.25  4722.1 2138.36  4736.6 2144.34  4809.1 2145.07  4836.6 2145.19
  4878.3 2141.14  4936.6 2142.28    4972 2138.83  4978.2 2134.81  4986.6 2135.03
  4996.6  2131.2  4997.1  2130.7  5017.8  2131.2  5021.4 2133.46  5042.3 2135.53
  5049.8 2140.85  5056.5 2142.77  5113.3 2145.73  5148.5 2153.08  5403.7 2170.52
#Mann= 9 ,-1 , 0
  3086.1     .07       0  3312.5    .035       0  3923.9     .07       0
  4449.6     .16       0  4466.6     .07       0  4656.4     .16       0
  4809.1     .07       0  4996.6     .07       0  5017.8     .07       0
#XS Ineff= 2 , 0
         4814.72 2151.11
Permanent Ineff=
       F       F
Bank Sta=4996.6,5017.8
XS Rating Curve= 0 ,0
Exp/Cntr=0.3,0.1

Type RM Length L Ch R = 1 ,14318   ,598,598,598
BEGIN DESCRIPTION:
Bitter Creek Trib14 19.0
END DESCRIPTION:
XS GIS Cut Line= 3
      1403904.97      6839738.02      1405488.29      6838471.43
        1405505.      6837988.02
#Sta/Elev= 30
  2972.4 2187.31  3136.5 2183.39  3171.7 2180.43  3221.4  2172.9  3335.3 2164.85
  3341.1 2164.75  3444.2 2157.74  3727.2 2150.73  4074.6 2146.64  4088.9 2147.77
  4537.2 2144.34  4857.4 2144.04  4900.6 2142.28  4935.8 2137.53  4985.4  2138.9
  4993.4 2137.65    5002 2128.45  5002.5 2127.95  5024.8 2128.45  5043.5 2134.69
  5048.9 2139.46  5057.7 2140.01  5093.5  2138.2  5143.5 2139.53  5183.5  2145.7
  5223.6 2146.16  5293.6 2150.85  5313.6 2150.04  5343.1 2153.43  5483.7 2164.07
#Mann= 9 ,-1 , 0
  2972.4     .07       0  3335.3    .035       0  3341.1     .07       0
  3444.2    .035       0  4088.9     .07       0    5002     .07       0
  5024.8     .07       0  5057.7     .16       0  5343.1     .07       0
Bank Sta=5002,5024.8
XS Rating Curve= 0 ,0
Exp/Cntr=0.3,0.1

Type RM Length L Ch R = 1 ,13720   ,648,648,648
BEGIN DESCRIPTION:
Bitter Creek Trib14 18.0
END DESCRIPTION:
XS GIS Cut Line= 3
      1404505.01      6839587.99       1405964.7      6838798.76
        1406505.      6837987.99
#Sta/Elev= 30
  3340.6 2176.87  3370.6 2176.24  3396.1 2171.48  3414.3  2167.7  3442.9 2167.24
  3488.4 2159.87  3583.7 2153.65  3693.1 2148.95  3738.5    2150  3970.2 2145.79
  4071.5 2144.86  4267.4 2143.71  4714.1 2141.65  4852.5 2138.85  4920.8 2135.97
  4954.9 2128.72  4965.3 2128.73  4966.1 2126.33  4966.6 2125.83    4989 2126.33
  4997.3 2135.93  5057.8 2135.59  5080.3 2135.45  5101.4 2139.07  5116.4 2136.99
  5122.4 2139.92  5125.9 2139.12    5483 2146.69  5685.9 2158.62  5974.3 2170.45
#Mann= 9 ,-1 , 0
  3340.6     .07       0  3396.1    .035       0  3970.2     .07       0
  4071.5    .035       0  4267.4     .07       0  4966.1     .07       0
    4989     .07       0  5057.8     .16       0  5125.9     .07       0
Bank Sta=4966.1,4989
XS Rating Curve= 0 ,0
Exp/Cntr=0.3,0.1

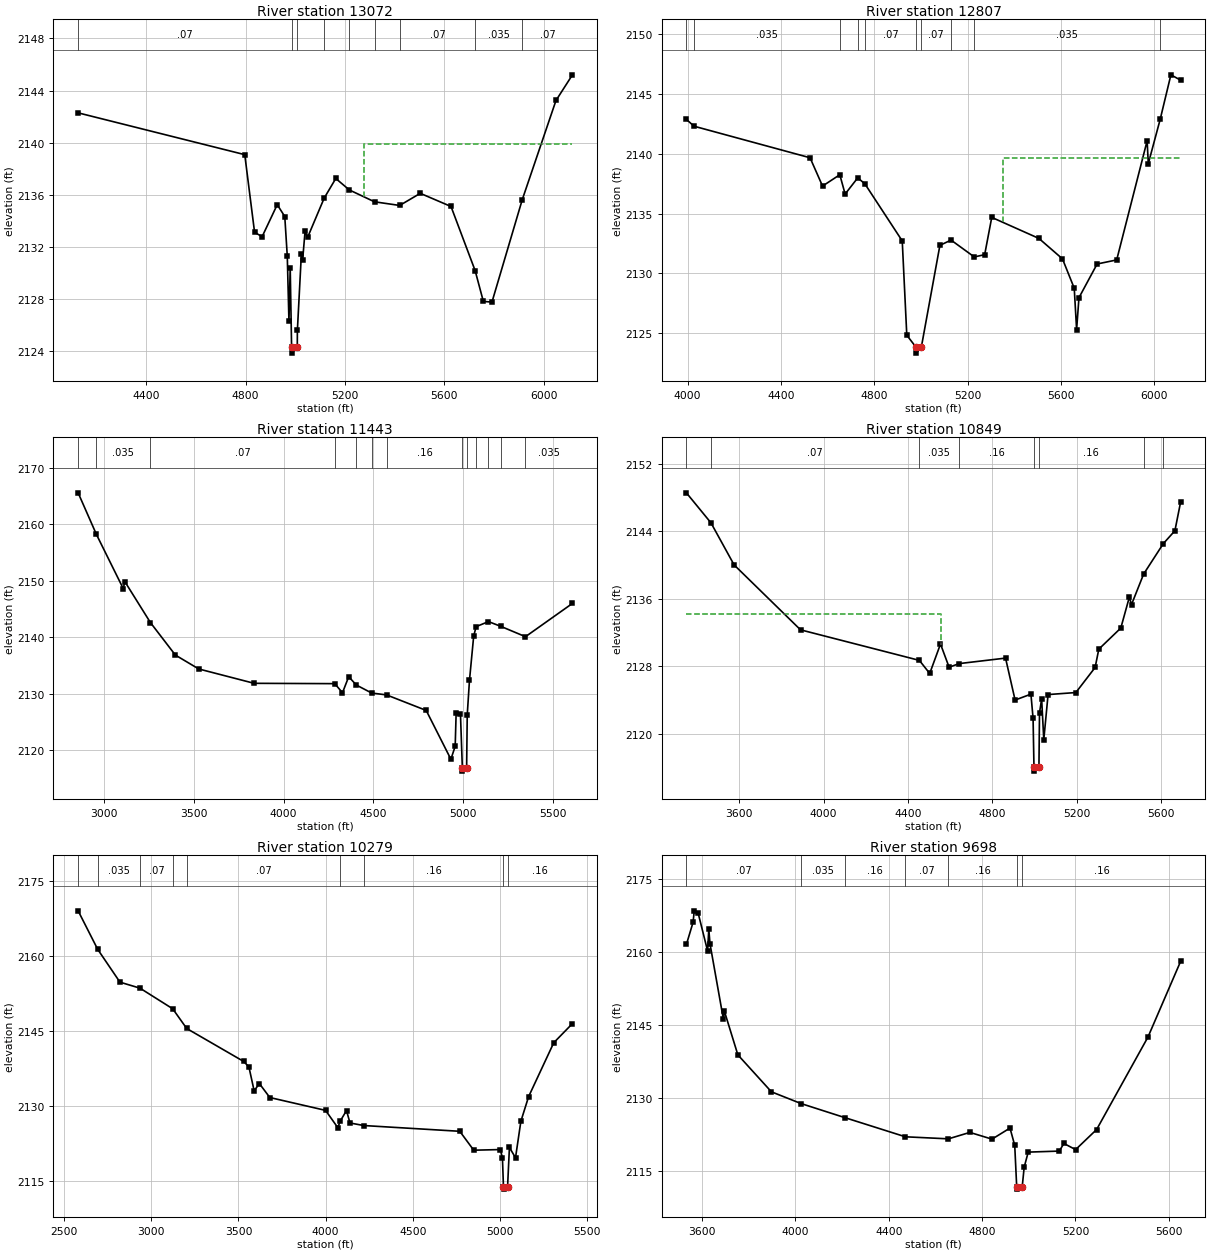
Type RM Length L Ch R = 1 ,13072   ,265,265,265
BEGIN DESCRIPTION:
Bitter Creek Trib14 17.0
END DESCRIPTION:
XS GIS Cut Line= 4
       1405494.7      6839128.52        1405724.      6839172.14
      1406356.87      6839276.91       1407439.3      6839550.62
#Sta/Elev= 30
  4125.1 2142.29  4796.4 2139.08  4835.9 2133.12  4866.3 2132.78  4927.2 2135.24
  4957.6 2134.33  4967.7 2131.28  4974.4 2126.28  4979.5 2130.39    4985 2124.34
  4985.5 2123.84    5008 2124.34  5008.4 2125.59  5024.4 2131.43  5029.5    2131
  5039.3 2133.18  5049.6 2132.73  5116.3 2135.74  5163.1 2137.25  5217.7 2136.37
  5319.1 2135.46  5420.5 2135.18  5503.5 2136.11  5627.3  2135.1  5724.6 2130.17
  5757.6 2127.81  5792.3 2127.76  5914.1 2135.61  6050.2 2143.24  6116.5 2145.21
#Mann= 9 ,-1 , 0
  4125.1     .07       0    4985     .07       0    5008     .07       0
  5116.3     .16       0  5217.7     .07       0  5319.1     .16       0
  5420.5     .07       0  5724.6    .035       0  5914.1     .07       0
#XS Ineff= 2 , 0
                         5276.65         2139.88
Permanent Ineff=
       F       F
Bank Sta=4985,5008
XS Rating Curve= 0 ,0
Exp/Cntr=0.3,0.1

Type RM Length L Ch R = 1 ,12807   ,1364,1364,1364
BEGIN DESCRIPTION:
Bitter Creek Trib14 16.0
END DESCRIPTION:
XS GIS Cut Line= 4
        1405447.      6839323.84      1405668.11      6839369.41
      1406434.72      6839508.03      1407536.57      6839662.37
#Sta/Elev= 30
  3995.2 2142.89  4027.9 2142.32  4524.9 2139.68  4578.4 2137.31  4652.4 2138.26
  4675.1 2136.64  4729.2    2138  4759.7  2137.5  4919.8 2132.72  4939.3 2124.83
  4978.6 2123.83  4979.1 2123.33  5001.6 2123.83  5081.1 2132.35  5128.9 2132.79
  5228.4 2131.38  5272.9 2131.57  5303.2 2134.69  5505.2 2132.93  5606.1 2131.22
  5656.6 2128.76  5666.7  2125.3  5676.8 2127.97  5754.6 2130.79  5838.4 2131.13
  5968.8  2141.1  5973.8 2139.19  6024.9 2142.91  6070.6 2146.62  6112.6 2146.17
#Mann= 10 ,-1 , 0
  3995.2     .07       0  4027.9    .035       0  4652.4     .07       0
  4729.2    .035       0  4759.7     .07       0  4978.6     .07       0
  5001.6     .07       0  5128.9     .16       0  5228.4    .035       0
  6024.9     .16       0
#XS Ineff= 2 , 0
                         5351.78         2139.63
Permanent Ineff=
       F       F
Bank Sta=4978.6,5001.6
XS Rating Curve= 0 ,0
Exp/Cntr=0.3,0.1

Type RM Length L Ch R = 1 ,11443   ,594,594,594
BEGIN DESCRIPTION:
Bitter Creek Trib14 15.0
END DESCRIPTION:
XS GIS Cut Line= 3
      1405554.97      6840738.01      1407535.25      6839917.59
      1407856.76      6839401.43
#Sta/Elev= 30
  2856.5 2165.54  2958.4 2158.17  3107.8 2148.58  3116.3 2149.84  3258.9 2142.58
  3397.7 2136.83  3527.9 2134.37  3836.2 2131.83  4285.2 2131.77    4328 2130.16
  4362.7    2133  4404.9 2131.53  4490.6 2130.11  4573.4 2129.78  4794.1 2127.03
  4931.5 2118.39  4955.4 2120.69  4960.8 2126.66  4984.7 2126.45  4995.4 2116.79
  4995.9 2116.29    5019 2116.79  5022.5 2126.25  5034.9 2132.34  5058.4 2140.19
  5071.9 2141.86  5140.8 2142.75  5207.8 2141.93  5346.7 2140.08  5608.1 2145.97
#Mann= 13 ,-1 , 0
  2856.5     .07       0  2958.4    .035       0  3258.9     .07       0
  4285.2    .035       0  4404.9     .07       0  4490.6    .035       0
  4573.4     .16       0  4995.4     .07       0    5019     .16       0
  5071.9    .035       0  5140.8     .16       0  5207.8     .07       0
  5346.7    .035       0
Bank Sta=4995.4,5019
XS Rating Curve= 0 ,0
Exp/Cntr=0.3,0.1

Type RM Length L Ch R = 1 ,10849   ,570,570,570
BEGIN DESCRIPTION:
Bitter Creek Trib14 14.0
END DESCRIPTION:
XS GIS Cut Line= 3
      1405904.96      6840738.01      1407521.56       6840404.7
      1408204.96      6840288.01
#Sta/Elev= 30
  3349.4 2148.56    3466    2145  3575.7 2140.02  3890.6 2132.33  4454.1 2128.71
  4503.2 2127.16  4554.3 2130.65  4595.1  2127.9  4643.2 2128.33  4862.8 2128.98
    4908 2124.01  4983.1 2124.71  4993.3 2121.84  4997.5 2116.09    4998 2115.59
  5021.1 2116.09  5023.8  2122.5  5033.9 2124.14  5044.1 2119.31  5064.4 2124.66
  5196.2  2124.9  5287.5 2127.87    5305 2130.04  5409.3 2132.54  5449.9 2136.21
    5460 2135.32  5517.6 2138.94  5610.8 2142.54  5665.8 2144.07  5693.3 2147.52
#Mann= 8 ,-1 , 0
  3349.4    .035       0    3466     .07       0  4454.1    .035       0
  4643.2     .16       0  4997.5     .07       0  5021.1     .16       0
  5517.6     .07       0  5610.8    .035       0
#XS Ineff= 2 , 0
         4556.35 2134.16
Permanent Ineff=
       F       F
Bank Sta=4997.5,5021.1
XS Rating Curve= 0 ,0
Exp/Cntr=0.3,0.1

Type RM Length L Ch R = 1 ,10279   ,581,581,581
BEGIN DESCRIPTION:
Bitter Creek Trib14 13.0
END DESCRIPTION:
XS GIS Cut Line= 3
      1405505.03        6840788.      1407924.84      6840808.39
        1408305.        6840638.
#Sta/Elev= 30
  2580.1 2169.01  2692.4 2161.31  2820.1 2154.75  2935.2 2153.55  3122.8 2149.43
  3203.2 2145.49  3530.1  2138.9  3560.1 2137.81  3590.1 2133.03  3620.1 2134.48
  3680.1 2131.69  4000.1 2129.12  4070.1 2125.67  4084.3 2126.99  4120.1 2129.09
  4140.1  2126.6  4219.9 2126.09  4770.2 2124.94  4850.2 2121.16  5002.8 2121.29
  5014.9 2119.65  5020.7 2113.88  5021.2 2113.38  5044.4 2113.88    5055 2121.71
  5089.9 2119.65  5120.7 2126.94    5165 2131.86  5309.5 2142.65  5416.6 2146.47
#Mann= 9 ,-1 , 0
  2580.1     .07       0  2692.4    .035       0  2935.2     .07       0
  3122.8    .035       0  3203.2     .07       0  4084.3    .035       0
  4219.9     .16       0  5020.7     .07       0  5044.4     .16       0
Bank Sta=5020.7,5044.4
XS Rating Curve= 0 ,0
Exp/Cntr=0.3,0.1

Type RM Length L Ch R = 1 ,9698    ,599,599,599
BEGIN DESCRIPTION:
Bitter Creek Trib14 12.0
END DESCRIPTION:
XS GIS Cut Line= 3
      1406455.01        6840938.       1407904.3      6841167.85
      1408555.01        6841138.
#Sta/Elev= 30
  3532.6 2161.49  3561.2 2166.03  3566.3 2168.39  3583.2 2167.89  3623.5 2160.16
  3628.6 2164.65  3633.8 2161.63  3690.9 2146.25  3695.9 2147.75  3753.2 2138.86
  3897.1 2131.28  4024.3 2128.87  4210.4 2126.01  4471.3 2122.06  4655.8 2121.64
  4747.6 2122.96  4842.6 2121.58  4919.7 2123.85    4940  2120.3  4948.4 2111.83
  4948.9 2111.33  4972.1 2111.83  4980.5 2115.83  4997.8 2118.92  5130.8 2119.13
  5150.9 2120.69  5200.9 2119.43    5291 2123.55  5511.2 2142.52  5651.4 2158.07
#Mann= 7 ,-1 , 0
  3532.6     .07       0  4024.3    .035       0  4210.4     .16       0
  4471.3     .07       0  4655.8     .16       0  4948.4     .07       0
  4972.1     .16       0
Bank Sta=4948.4,4972.1
XS Rating Curve= 0 ,0
Exp/Cntr=0.3,0.1

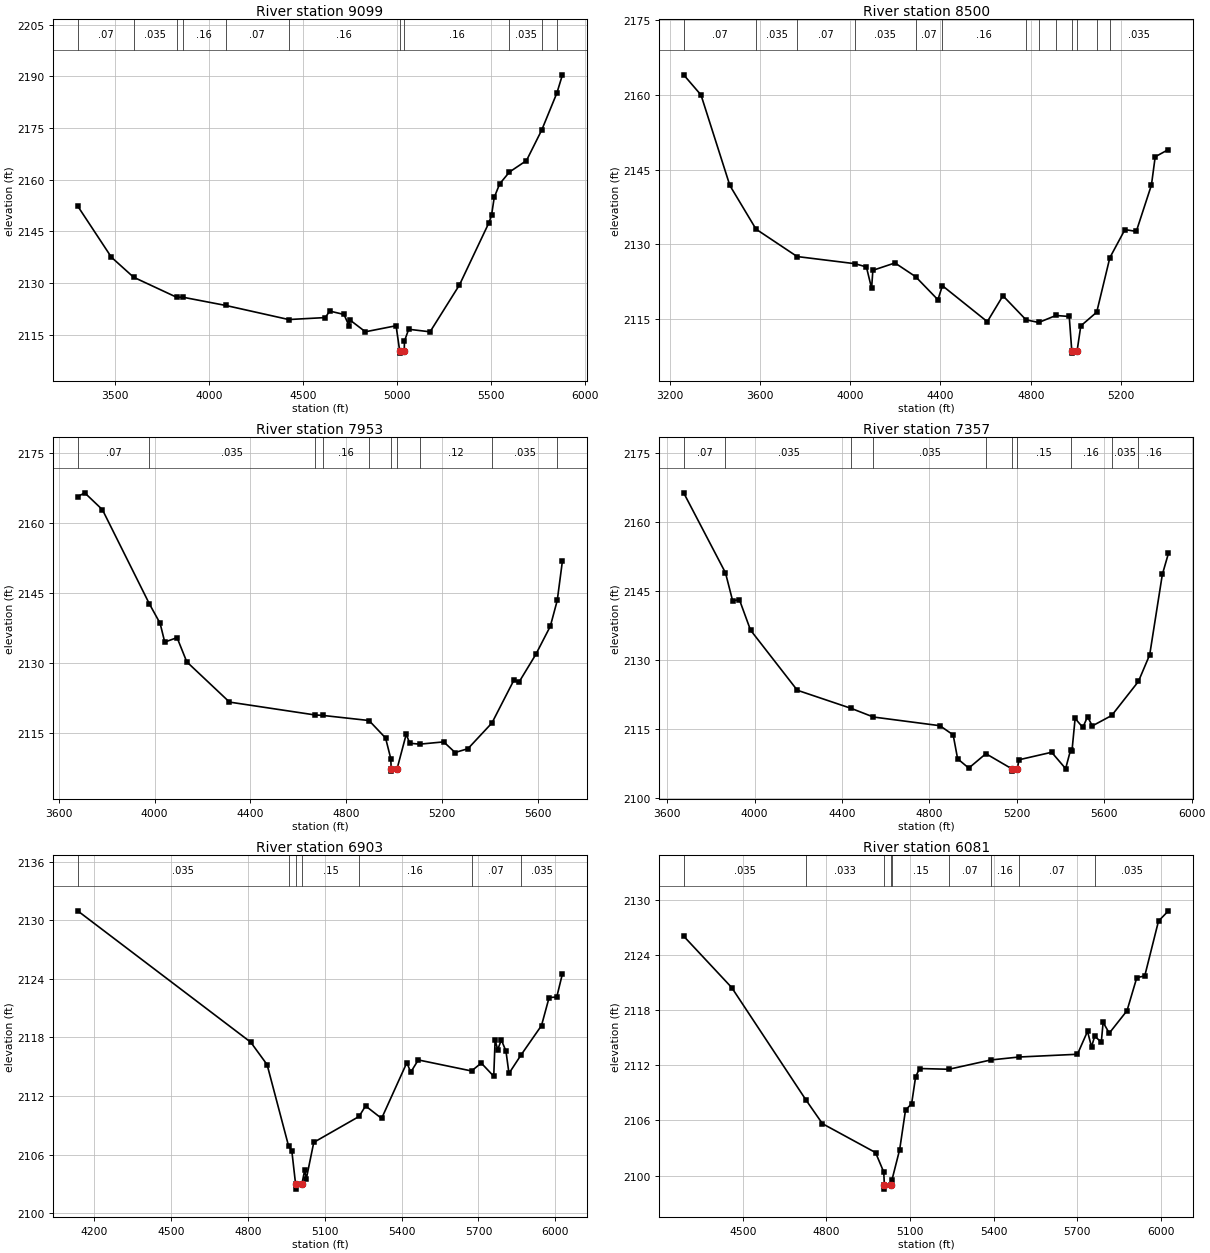
Type RM Length L Ch R = 1 ,9099    ,599,599,599
BEGIN DESCRIPTION:
Bitter Creek Trib14 11.0
END DESCRIPTION:
XS GIS Cut Line= 3
      1406604.99        6841088.      1408213.51      6841634.43
      1408904.97      6841088.02
#Sta/Elev= 30
  3301.2 2152.37  3480.8 2137.52  3598.7 2131.73  3828.8 2125.89  3860.6 2125.93
  4089.8 2123.53  4424.5 2119.45  4619.3 2120.02  4642.5 2121.91  4718.7 2120.92
  4744.8 2117.72  4750.1 2119.33  4832.6  2115.9  4995.9 2117.65  5015.5 2110.21
    5016 2109.71  5039.3 2110.21  5040.5 2113.22    5063 2116.63  5176.8 2115.89
  5333.3 2129.49  5489.4 2147.45  5503.8 2149.64  5518.3 2154.86  5547.1 2158.78
  5599.1 2162.22  5689.8 2165.54  5771.3 2174.43  5851.9 2185.16  5881.3 2190.41
#Mann= 11 ,-1 , 0
  3301.2     .07       0  3598.7    .035       0  3828.8     .07       0
  3860.6     .16       0  4089.8     .07       0  4424.5     .16       0
  5015.5     .07       0  5039.3     .16       0  5599.1    .035       0
  5771.3     .16       0  5851.9     .07       0
Bank Sta=5015.5,5039.3
XS Rating Curve= 0 ,0
Exp/Cntr=0.3,0.1

Type RM Length L Ch R = 1 ,8500    ,547,547,547
BEGIN DESCRIPTION:
Bitter Creek Trib14 10.0
END DESCRIPTION:
XS GIS Cut Line= 3
        1406555.        6841238.      1408138.29      6841954.57
      1408504.98      6842137.99
#Sta/Elev= 30
  3262.1 2163.99  3338.9 2159.95  3466.7  2141.8  3582.6 2133.04  3764.9 2127.54
  4020.4 2126.11  4071.7 2125.46  4094.8 2121.16  4100.3 2124.78  4198.2 2126.26
  4289.6 2123.51  4388.5 2118.88  4408.5 2121.69  4607.4 2114.48  4676.7 2119.68
  4779.2 2114.84  4835.3 2114.32  4911.4 2115.72  4970.4 2115.52  4981.6 2108.67
  4982.1 2108.17  5005.4 2108.67  5021.6 2113.63  5092.1 2116.38  5150.3 2127.31
  5217.2 2132.95  5267.5 2132.58  5334.6 2141.89  5351.3 2147.55    5410 2149.01
#Mann= 13 ,-1 , 0
  3262.1     .07       0  3582.6    .035       0  3764.9     .07       0
  4020.4    .035       0  4289.6     .07       0  4408.5     .16       0
  4779.2     .12       0  4835.3     .16       0  4911.4     .12       0
  4981.6     .07       0  5005.4     .12       0  5092.1     .16       0
  5150.3    .035       0
Bank Sta=4981.6,5005.4
XS Rating Curve= 0 ,0
Exp/Cntr=0.3,0.1

Type RM Length L Ch R = 1 ,7953    ,596,596,596
BEGIN DESCRIPTION:
Bitter Creek Trib14 9.0
END DESCRIPTION:
XS GIS Cut Line= 3
      1406554.96      6842588.01      1407860.68      6842390.31
      1408554.98        6842288.
#Sta/Elev= 30
  3679.4 2165.71  3708.8 2166.55  3782.6 2162.94  3978.6 2142.74  4023.3 2138.58
  4042.7 2134.55  4094.1 2135.51  4134.6 2130.32  4312.8 2121.69  4668.7 2118.94
    4704 2118.82  4894.8 2117.74  4963.9    2114  4985.6 2109.57  4987.5 2107.39
    4988 2106.89  5011.9 2107.39    5050 2114.77    5065 2112.87  5106.1 2112.67
  5206.5 2113.16    5254 2110.88  5307.6  2111.7  5407.6 2117.21  5499.7 2126.43
  5519.9 2125.91  5590.6  2131.9  5651.3 2137.96  5680.1 2143.48  5701.8 2151.96
#Mann= 10 ,-1 , 0
  3679.4     .07       0  3978.6    .035       0  4668.7     .07       0
    4704     .16       0  4894.8     .12       0  4987.5     .07       0
  5011.9     .12       0  5106.1     .12       0  5407.6    .035       0
  5680.1     .16       0
Bank Sta=4987.5,5011.9
XS Rating Curve= 0 ,0
Exp/Cntr=0.3,0.1

Type RM Length L Ch R = 1 ,7357    ,454,454,454
BEGIN DESCRIPTION:
Bitter Creek Trib14 8.0
END DESCRIPTION:
XS GIS Cut Line= 3
      1406604.98        6842688.      1407904.56      6842943.18
      1408605.02      6842387.99
#Sta/Elev= 30
  3675.6 2166.42  3866.9 2148.99  3899.8 2142.86  3930.4 2143.17  3981.4 2136.51
  4195.4  2123.4  4443.5 2119.42  4543.8 2117.56    4848 2115.67  4908.7 2113.67
  4929.1 2108.46  4980.1 2106.43  5058.5 2109.57  5177.3 2106.27  5177.8 2105.77
  5201.8 2106.27  5210.3 2108.25  5359.3 2109.88  5423.4 2106.31  5446.3 2110.46
  5452.3 2110.14  5466.7 2117.25    5502 2115.29  5523.7 2117.63  5545.3 2115.62
  5634.2  2117.9  5756.3 2125.31    5808 2131.13  5865.8 2148.63  5893.8 2153.24
#Mann= 10 ,-1 , 0
  3675.6     .07       0  3866.9    .035       0  4443.5     .07       0
  4543.8    .035       0  5058.5     .15       0  5177.3    .035       0
  5201.8     .15       0  5446.3     .16       0  5634.2    .035       0
  5756.3     .16       0
Bank Sta=5177.3,5201.8
XS Rating Curve= 0 ,0
Exp/Cntr=0.3,0.1

Type RM Length L Ch R = 1 ,6903    ,822,822,822
BEGIN DESCRIPTION:
Bitter Creek Trib14 7.0
END DESCRIPTION:
XS GIS Cut Line= 3
      1406940.92      6843256.96      1407804.12      6843322.64
      1408760.17      6842944.54
#Sta/Elev= 30
  4134.3 2130.96  4810.3 2117.51  4874.3 2115.21    4958  2106.9  4970.8  2106.4
  4985.7 2102.96  4986.2 2102.46  5010.2 2102.96  5021.6 2104.46    5027 2103.45
  5056.7 2107.25  5233.5  2109.9    5259 2110.98  5321.7  2109.7  5420.3 2115.41
  5435.3 2114.43    5465 2115.69    5673 2114.56    5711 2115.37  5759.7 2114.02
  5765.1 2117.72  5775.2 2116.74  5789.4 2117.74  5807.5 2116.59  5819.2 2114.31
  5866.4  2116.2  5946.3 2119.21    5976 2122.08  6005.8 2122.13  6028.1 2124.52
#Mann= 7 ,-1 , 0
  4134.3    .035       0    4958     .15       0  4985.7     .07       0
  5010.2     .15       0  5233.5     .16       0    5673     .07       0
  5866.4    .035       0
Bank Sta=4985.7,5010.2
XS Rating Curve= 0 ,0
Exp/Cntr=0.3,0.1

Type RM Length L Ch R = 1 ,6081    ,459,459,459
BEGIN DESCRIPTION:
Bitter Creek Trib14 6.0
END DESCRIPTION:
XS GIS Cut Line= 3
      1407513.82      6844062.53      1408138.73      6843720.69
      1408805.02      6842937.98
#Sta/Elev= 30
  4287.7 2126.02    4460 2120.44  4726.8 2108.22  4785.8 2105.65  4976.5 2102.51
    5006 2100.39    5008 2099.04  5008.5 2098.54  5032.6 2099.04  5035.4 2099.54
  5063.1 2102.84    5084 2107.12    5106 2107.82  5120.3 2110.74  5134.5 2111.64
  5239.8 2111.56  5390.1 2112.57  5491.2 2112.89  5701.2 2113.19  5737.4 2115.68
  5751.7 2113.99  5763.2 2115.16  5786.8  2114.5  5793.4 2116.66  5815.4 2115.48
  5879.1 2117.92  5914.2 2121.51  5942.8  2121.7  5992.2 2127.66  6027.9 2128.77
#Mann= 9 ,-1 , 0
  4287.7    .035       0  4726.8    .033       0    5008    .033       0
  5032.6    .033       0  5035.4     .15       0  5239.8     .07       0
  5390.1     .16       0  5491.2     .07       0  5763.2    .035       0
Bank Sta=5008,5032.6
XS Rating Curve= 0 ,0
Exp/Cntr=0.3,0.1

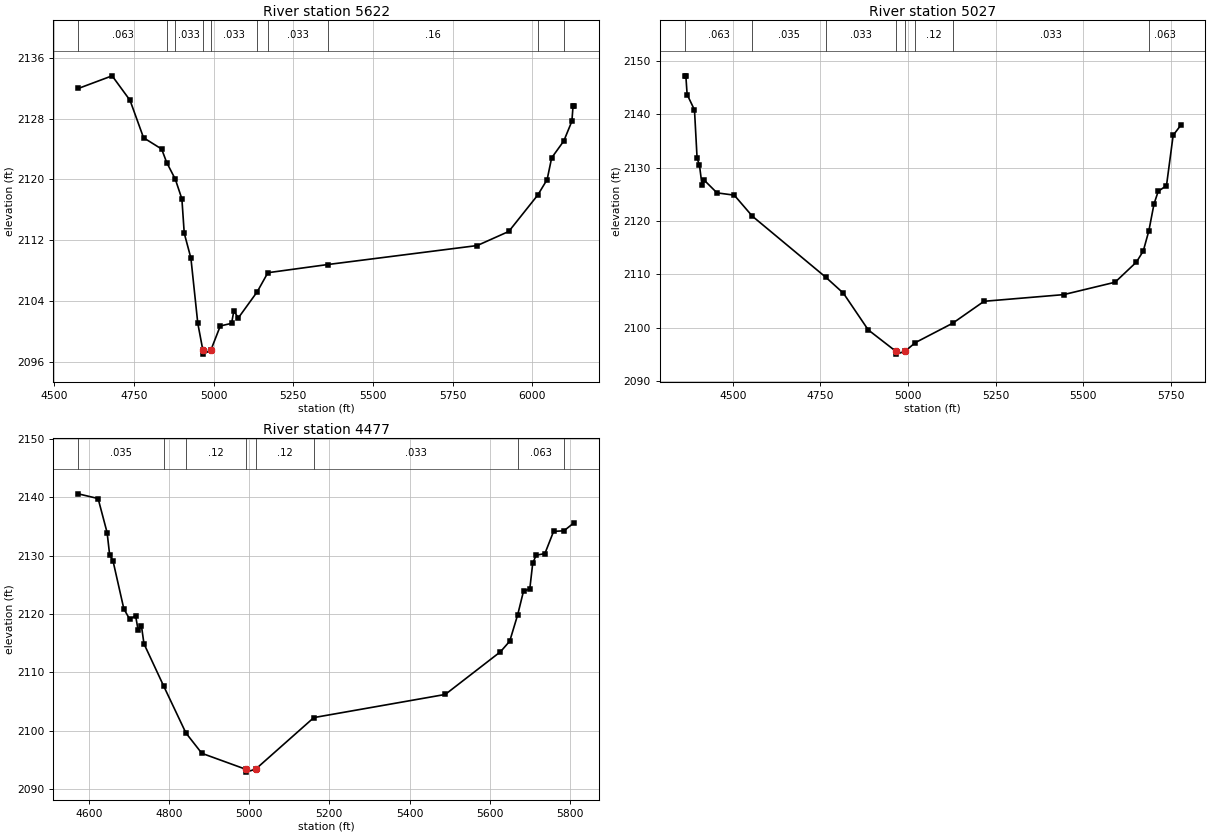
Type RM Length L Ch R = 1 ,5622    ,595,595,595
BEGIN DESCRIPTION:
Bitter Creek Trib14 5.0
END DESCRIPTION:
XS GIS Cut Line= 3
      1407905.01      6844437.99      1408218.56      6844151.24
        1409005.        6843338.
#Sta/Elev= 30
  4575.1 2131.99  4681.5 2133.66  4737.7 2130.43  4780.1  2125.5  4836.9 2124.01
  4852.8 2122.23  4879.9 2120.02  4900.4 2117.44  4907.8 2112.92  4928.7 2109.63
  4950.3 2101.05  4966.3 2097.48  4966.8 2096.98  4991.1 2097.48  5020.9 2100.69
  5056.4 2101.04  5063.4 2102.67  5077.5 2101.75  5136.7 2105.19  5170.2 2107.71
  5358.5 2108.79  5827.1 2111.29  5926.2 2113.15  6017.2 2117.95  6046.5 2119.99
  6060.7 2122.85  6098.9 2125.08  6124.2 2127.68  6127.8 2129.66  6131.3 2129.66
#Mann= 10 ,-1 , 0
  4575.1    .063       0  4852.8    .035       0  4879.9    .033       0
  4966.3    .033       0  4991.1    .033       0  5136.7     .15       0
  5170.2    .033       0  5358.5     .16       0  6017.2    .035       0
  6098.9    .063       0
Bank Sta=4966.3,4991.1
XS Rating Curve= 0 ,0
Exp/Cntr=0.3,0.1

Type RM Length L Ch R = 1 ,5027    ,550,550,550
BEGIN DESCRIPTION:
Bitter Creek Trib14 4.0
END DESCRIPTION:
XS GIS Cut Line= 3
      1408105.03      6845037.97      1408575.31      6844607.87
      1409305.01        6844338.
#Sta/Elev= 30
  4362.7 2147.18    4366 2147.18  4369.7 2143.68  4390.7 2140.79  4398.1 2131.76
  4404.9 2130.44  4412.3 2126.67  4419.1  2127.6  4454.9 2125.27  4504.2 2124.84
  4555.7 2120.91  4765.8 2109.45  4815.6 2106.49  4886.5 2099.62    4966 2095.58
  4966.5 2095.08  4990.9 2095.58  5020.9 2097.23  5127.6 2100.87    5217 2104.97
  5444.3 2106.22    5591 2108.54  5651.8 2112.31  5671.4 2114.38  5687.4 2118.18
    5702 2123.18    5714 2125.55  5737.7 2126.64  5756.7 2136.05    5778 2137.89
#Mann= 8 ,-1 , 0
  4362.7    .063       0  4555.7    .035       0  4765.8    .033       0
    4966    .033       0  4990.9    .033       0  5020.9     .12       0
  5127.6    .033       0  5687.4    .063       0
Bank Sta=4966,4990.9
XS Rating Curve= 0 ,0
Exp/Cntr=0.3,0.1

Type RM Length L Ch R = 1 ,4477    ,597,597,597
BEGIN DESCRIPTION:
Bitter Creek Trib14 3.0
END DESCRIPTION:
XS GIS Cut Line= 3
      1408455.03      6845337.97      1408798.89      6845085.82
      1409505.03      6844687.98
#Sta/Elev= 30
  4573.6 2140.62  4623.2 2139.81  4645.7 2133.96  4651.9 2130.19  4660.4  2129.1
  4687.4 2120.88  4702.1 2119.09  4716.7  2119.7  4722.9 2117.27  4731.4 2117.91
  4737.6 2114.89  4786.7 2107.64  4842.2 2099.58  4881.9 2096.09  4991.1 2093.36
  4991.6 2092.86    5016 2093.36  5161.3 2102.22    5489 2106.19  5626.8 2113.52
  5649.8 2115.33  5669.7 2119.87  5684.2 2123.92  5699.9 2124.31  5707.2 2128.72
  5715.8 2130.09  5737.5 2130.36  5759.2 2134.17  5785.2 2134.28  5810.5 2135.67
#Mann= 8 ,-1 , 0
  4573.6    .035       0  4786.7    .033       0  4842.2     .12       0
  4991.1     .07       0    5016     .12       0  5161.3    .033       0
  5669.7    .063       0  5785.2    .035       0
Bank Sta=4991.1,5016
XS Rating Curve= 0 ,0
Exp/Cntr=0.3,0.1