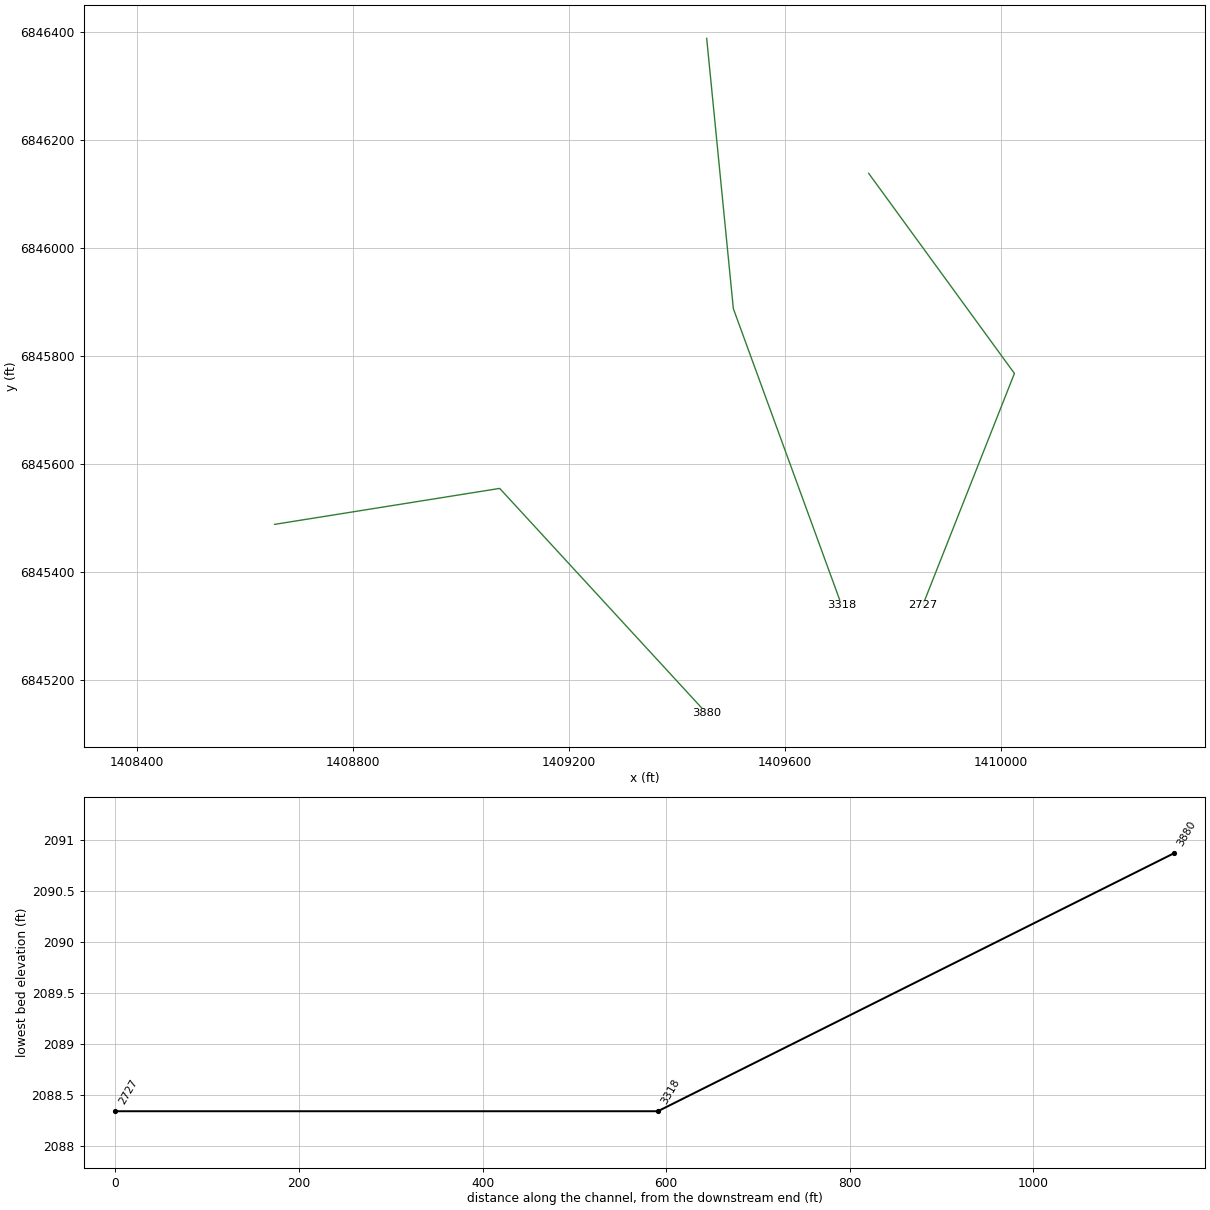
HEC-RAS study Bitter Creek Trib14.prj: Bitter Creek Trib14 Base Level Engineering

--- Bitter Creek Trib14.g01 (geometry) --- (continued)

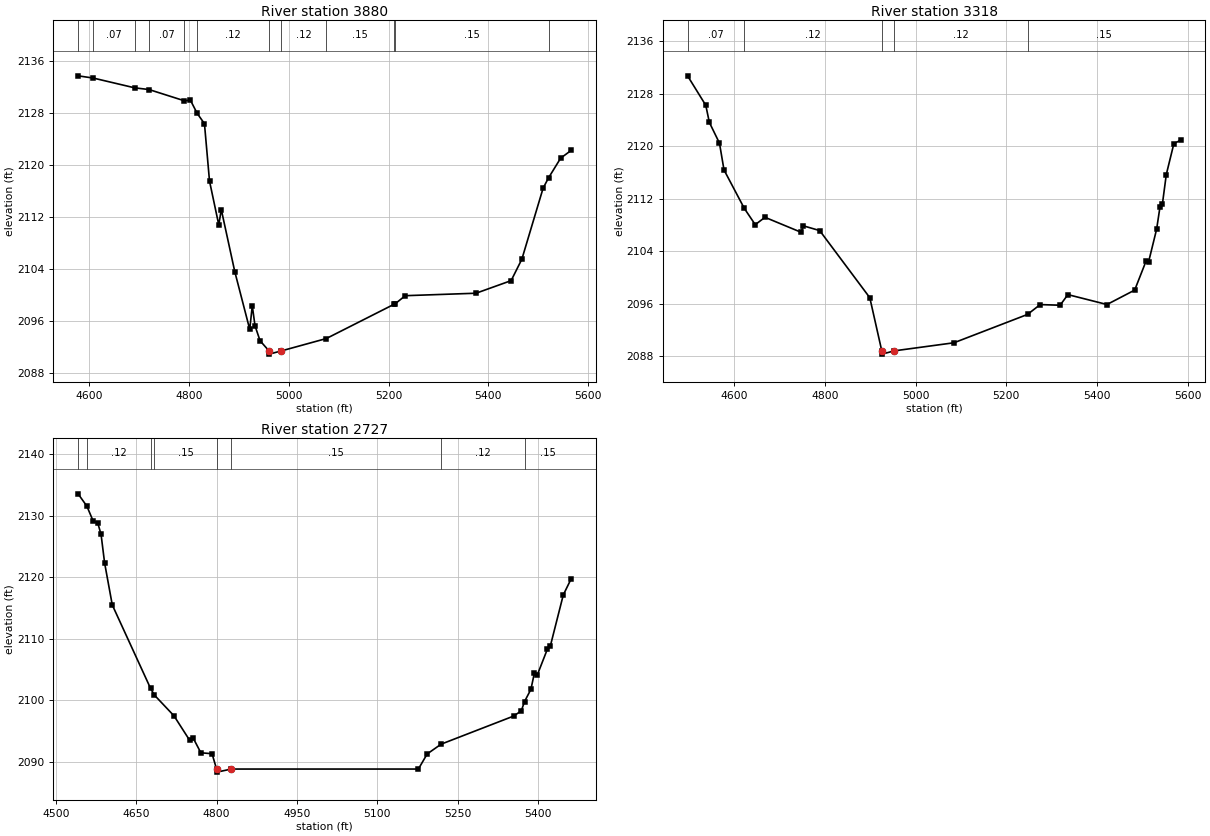
Type RM Length L Ch R = 1 ,3880    ,562,562,562
BEGIN DESCRIPTION:
Bitter Creek Trib14 2.0
END DESCRIPTION:
XS GIS Cut Line= 3
      1408654.99        6845488.       1409071.7      6845554.58
      1409455.01      6845137.99
#Sta/Elev= 30
    4578 2133.73  4608.8 2133.38  4691.4 2131.88    4720 2131.62  4791.2 2129.88
  4802.9    2130  4816.6 2127.95  4831.2 2126.36  4841.3 2117.53  4859.9 2110.77
  4864.9 2113.14  4891.9 2103.59  4921.9 2094.68    4927 2098.31  4932.5 2095.23
  4942.6 2092.93  4960.5 2091.37    4961 2090.87  4985.4 2091.37  5075.3 2093.27
  5210.6 2098.53  5213.1 2098.61  5233.5 2099.87  5375.3 2100.25  5445.6 2102.19
  5467.1 2105.49  5509.7 2116.44  5520.8 2118.05  5544.8 2121.05  5566.1 2122.26
#Mann= 12 ,-1 , 0
    4578    .035       0  4608.8     .07       0  4691.4     .12       0
    4720     .07       0  4791.2    .035       0  4816.6     .12       0
  4960.5     .07       0  4985.4     .12       0  5075.3     .15       0
  5210.6     .12       0  5213.1     .15       0  5520.8    .035       0
Bank Sta=4960.5,4985.4
XS Rating Curve= 0 ,0
Exp/Cntr=0.3,0.1

Type RM Length L Ch R = 1 ,3318    ,591,591,591
BEGIN DESCRIPTION:
Bitter Creek Trib14 1.0
END DESCRIPTION:
XS GIS Cut Line= 3
        1409455.      6846388.02      1409504.38      6845887.45
      1409704.99      6845338.03
#Sta/Elev= 30
    4497 2130.75  4537.2 2126.26  4545.1 2123.65  4567.4 2120.49  4577.4 2116.41
  4622.2 2110.55  4646.3 2108.07  4667.8 2109.19  4747.4 2106.91  4752.5 2107.89
  4788.4 2107.17    4899 2096.94  4925.4 2088.84  4925.9 2088.34    4953 2088.84
  5084.6 2090.07  5246.9 2094.39  5274.8 2095.89  5318.8 2095.79  5335.9 2097.41
  5422.2  2095.9  5483.3  2098.1  5508.6 2102.56  5513.9 2102.38  5531.7 2107.39
  5539.1 2110.78  5544.4  2111.2    5553 2115.71  5569.7 2120.42  5584.9 2120.95
#Mann= 5 ,-1 , 0
    4497     .07       0  4622.2     .12       0  4925.4     .07       0
    4953     .12       0  5246.9     .15       0
Bank Sta=4925.4,4953
XS Rating Curve= 0 ,0
Exp/Cntr=0.3,0.1

Type RM Length L Ch R = 1 ,2727    ,0,0,0
BEGIN DESCRIPTION:
Bitter Creek Trib15 7.0
END DESCRIPTION:
XS GIS Cut Line= 3
      1409754.99      6846138.01      1410024.87      6845767.48
      1409854.98      6845337.96
#Sta/Elev= 30
  4541.6 2133.53    4558 2131.53  4569.8  2129.1  4578.3 2128.81  4584.5 2126.93
  4591.1 2122.31  4605.4 2115.49  4676.8 2101.95  4683.9 2100.86  4720.5 2097.49
  4749.8 2093.51    4756 2093.94  4770.7 2091.48  4791.6 2091.33    4800 2088.84
  4800.5 2088.34  4827.6 2088.84  5176.6 2088.84    5193 2091.29    5219 2092.88
  5354.3 2097.44  5368.6 2098.29  5374.7  2099.8  5386.6 2101.79  5392.9 2104.37
  5398.3 2104.07  5417.3 2108.31  5422.6 2108.74    5447 2117.12  5461.9 2119.77
#Mann= 8 ,-1 , 0
  4541.6     .07       0    4558     .12       0  4676.8     .07       0
  4683.9     .15       0    4800     .07       0  4827.6     .15       0
    5219     .12       0  5374.7     .15       0
Bank Sta=4800,4827.6
XS Rating Curve= 0 ,0
Exp/Cntr=0.3,0.1

Chan Stop Cuts=-1
Use User Specified Reach Order=0
Composite Channel Slope=5