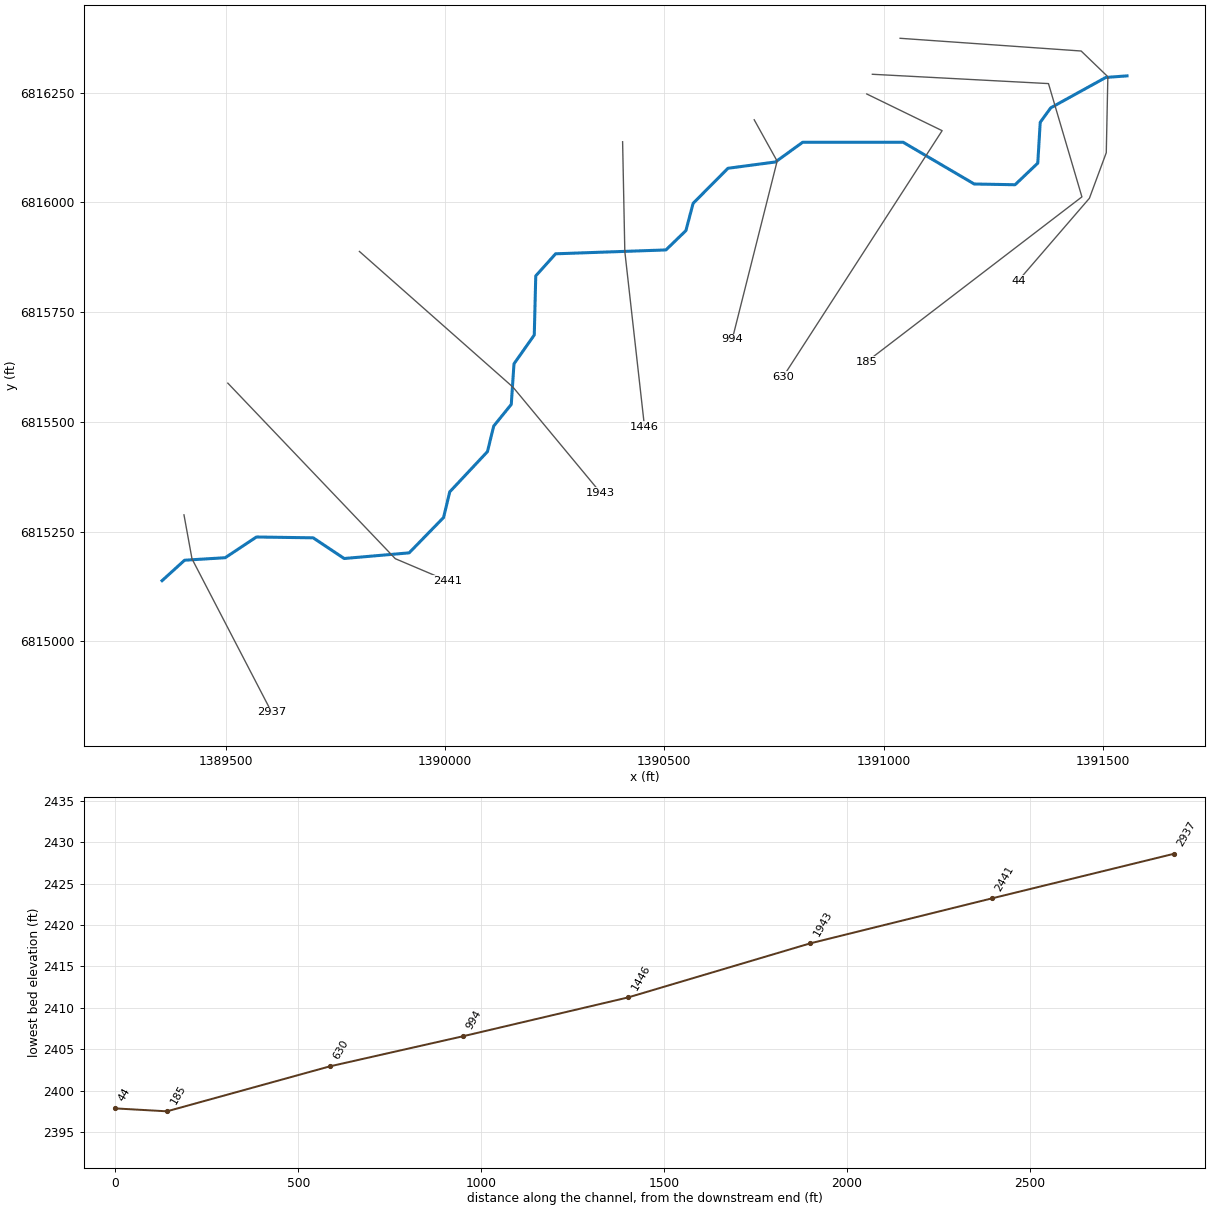
--- Bitter Creek Trib14T1.prj (project) ---

Proj Title=Bitter Creek Trib14T1 Base Level Engineering
Current Plan=p01
Default Exp/Contr=0.3,0.1
English Units
Geom File=g01
Flow File=f01
Plan File=p01
Y Axis Title=Elevation
X Axis Title(PF)=Main Channel Distance
X Axis Title(XS)=Station
BEGIN DESCRIPTION:
Bitter Creek Trib14T1
END DESCRIPTION:
DSS Export Rating Curves= 0
DSS Export Rating Curve Sorted= 0
DSS Export Volume Flow Curves= 0
DXF OffsetX= 0
DXF OffsetY= 0
DXF ScaleX= 1
DXF ScaleY= 10

--- Bitter Creek Trib14T1.p01 (plan) ---

Plan Title=Multiple Run
Short Identifier=Multiple
Geom File=g01
Flow File=f01
Subcritical Flow
K Sum by GR= 0
Std Step Tol= 0.01
Critical Tol= 0.01
Num of Std Step Trials= 20
Max Error Tol= 0.3
Flow Tol Ratio= 0.001
Split Flow NTrial= 30
Split Flow Tol= 0.02
Split Flow Ratio= 0.02
Log Output Level= 0
Friction Slope Method= 1
Unsteady Friction Slope Method= 2
Unsteady Bridges Friction Slope Method= 1
Parabolic Critical Depth
Global Vel Dist=  1 , 1 , 1
Global Log Level= 0
CheckData=True
Encroach Param= -1, 0, 0, 0
BEGIN DESCRIPTION:
Multiple Run
END DESCRIPTION:

--- Bitter Creek Trib14T1.f01 (steady flow) ---

Flow Title=Multiple
Number of Profiles=7
Profile Names=10-year,25-year,50-year,1pct_min,100-year,1pct_plu,500-year
River Rch & RM= Bitter Creek Tri,Reach-1,2937
     324     466     587     368     735    1466    1165
River Rch & RM= Bitter Creek Tri,Reach-1,2441
     324     463     582     364     726    1448    1143
Boundary for River Rch & Prof#=Bitter Creek Tri,Reach-1,1
Up Type=0
Dn Type=3
Dn Slope=0.005
Boundary for River Rch & Prof#=Bitter Creek Tri,Reach-1,2
Up Type=0
Dn Type=3
Dn Slope=0.005
Boundary for River Rch & Prof#=Bitter Creek Tri,Reach-1,3
Up Type=0
Dn Type=3
Dn Slope=0.005
Boundary for River Rch & Prof#=Bitter Creek Tri,Reach-1,4
Up Type=0
Dn Type=3
Dn Slope=0.005
Boundary for River Rch & Prof#=Bitter Creek Tri,Reach-1,5
Up Type=0
Dn Type=3
Dn Slope=0.005
Boundary for River Rch & Prof#=Bitter Creek Tri,Reach-1,6
Up Type=0
Dn Type=3
Dn Slope=0.005
Boundary for River Rch & Prof#=Bitter Creek Tri,Reach-1,7
Up Type=0
Dn Type=3
Dn Slope=0.005

--- Bitter Creek Trib14T1.g01 (geometry) ---

Geom Title=Existing Conditions

River Reach=Bitter Creek Tri,Reach-1
Reach XY= 30
      1389355.00      6815138.00      1389406.40      6815184.61
      1389499.04      6815190.32      1389570.22      6815237.50
      1389699.47      6815235.63      1389770.22      6815188.51
      1389918.34      6815201.36      1389996.85      6815281.93
      1390010.87      6815340.28      1390096.84      6815431.95
      1390111.14      6815490.17      1390151.17      6815539.58
      1390157.36      6815632.02      1390203.61      6815697.67
      1390206.98      6815832.35      1390252.26      6815882.66
      1390503.75      6815891.45      1390549.26      6815935.43
      1390565.78      6815997.68      1390645.19      6816077.49
      1390753.40      6816091.86      1390815.50      6816136.78
      1391044.50      6816136.80      1391206.59      6816041.67
      1391299.72      6816039.99      1391351.48      6816089.25
      1391357.08      6816182.29      1391381.04      6816215.20
      1391506.49      6816284.40      1391555.00      6816288.00

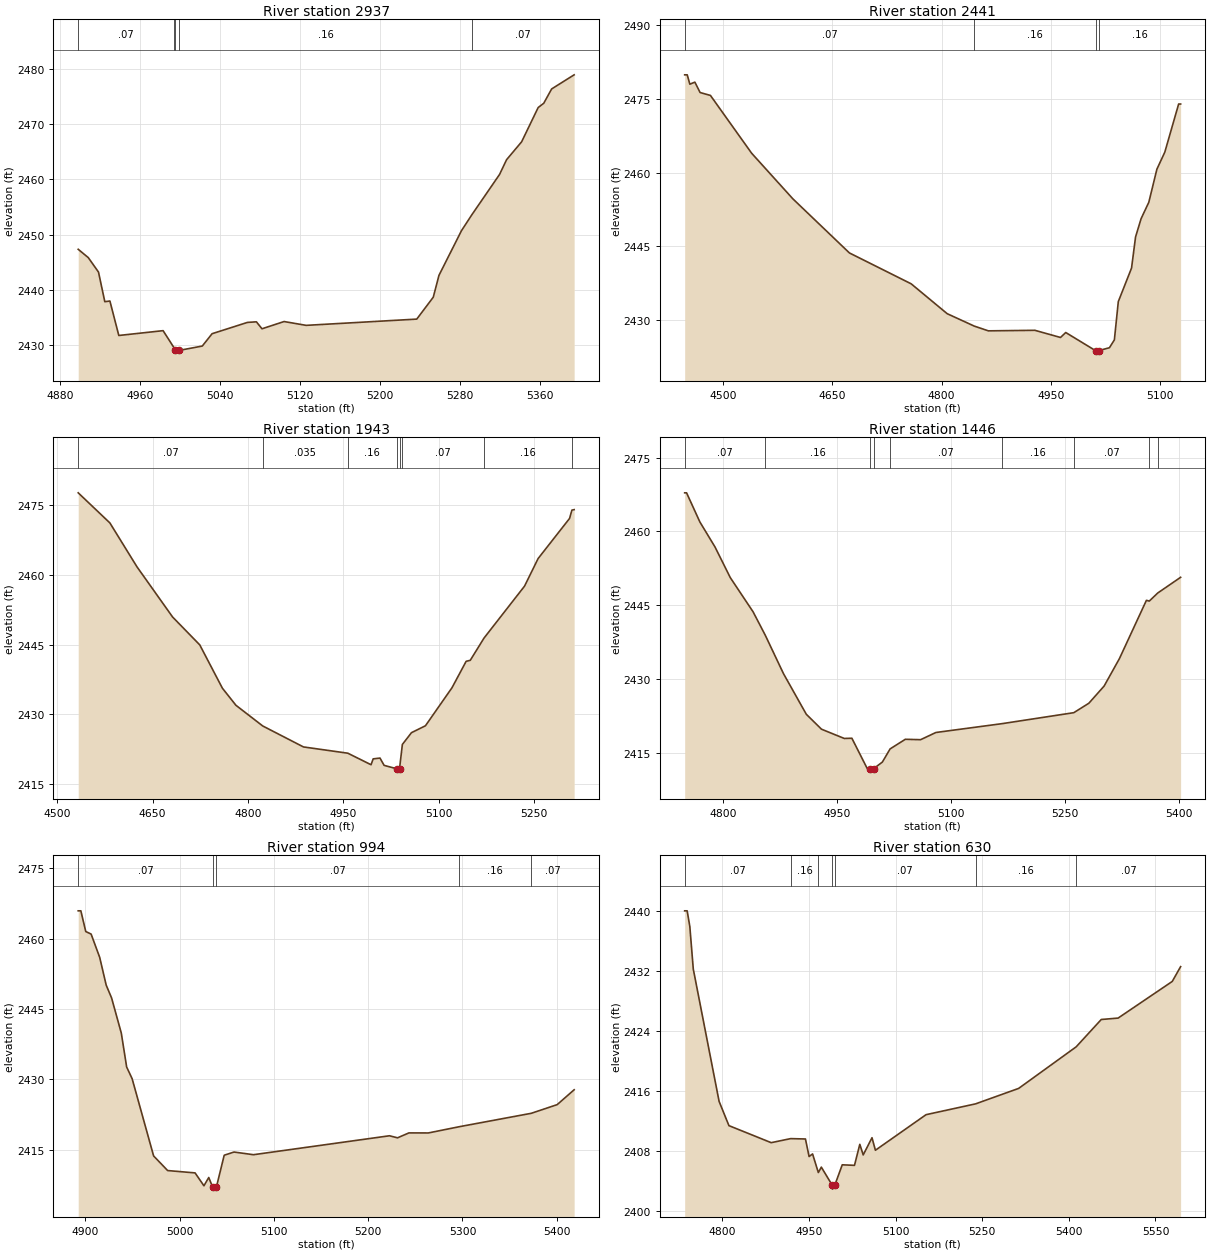
Type RM Length L Ch R = 1,2937,496,496,496
BEGIN DESCRIPTION:
Bitter Creek Trib14T1 4.0
END DESCRIPTION:
XS GIS Cut Line= 3
      1389405.01      6815287.95      1389423.30      6815187.71
      1389605.00      6814838.00
#Sta/Elev= 30
  4898.1 2447.35  4908.2 2445.84  4918.4 2443.23  4924.7 2437.88  4929.8 2438.00
  4938.7 2431.77  4983.0 2432.64  4993.5 2429.67  4995.3 2429.08  4995.6 2428.58
  4999.3 2429.08  5022.2 2429.86  5032.0 2432.09  5067.3 2434.13  5076.3 2434.24
  5081.9 2432.98  5104.0 2434.29  5126.1 2433.60  5236.7 2434.73  5253.2 2438.69
  5258.9 2442.64  5281.4 2450.71  5291.7 2453.57  5319.5 2460.88  5326.5 2463.54
  5341.6 2466.79  5358.1 2472.97  5363.7 2473.75  5371.6 2476.34  5394.1 2478.89
#Mann=5,-1,0
  4898.1    0.07       0  4993.5    0.16       0  4995.3    0.07       0
  4999.3    0.16       0  5291.7    0.07       0
Bank Sta=4995.3,4999.3
Exp/Cntr=0.3,0.1

Type RM Length L Ch R = 1,2441,498,498,498
BEGIN DESCRIPTION:
Bitter Creek Trib14T1 3.0
END DESCRIPTION:
XS GIS Cut Line= 3
      1389505.00      6815588.00      1389886.78      6815188.07
      1390005.01      6815137.99
#Sta/Elev= 30
  4447.1 2479.94  4450.6 2479.94  4454.2 2478.03  4461.1 2478.45  4468.3 2476.33
  4482.5 2475.74  4539.1 2463.96  4595.7 2454.67  4673.4 2443.64  4758.3 2437.34
  4807.7 2431.26  4844.9 2428.73  4864.3 2427.76  4928.2 2427.87  4963.4 2426.41
  4970.6 2427.42  5011.6 2423.72  5011.9 2423.22  5015.7 2423.72  5030.6 2424.32
  5037.4 2425.92  5042.8 2433.72  5061.0 2440.56  5066.5 2446.90  5074.1 2450.62
  5084.7 2453.96  5095.8 2460.70  5106.7 2464.19  5125.7 2473.99  5128.4 2473.99
#Mann=4,-1,0
  4447.1    0.07       0  4844.9    0.16       0  5011.6    0.07       0
  5015.7    0.16       0
Bank Sta=5011.6,5015.7
Exp/Cntr=0.3,0.1

Type RM Length L Ch R = 1,1943,497,497,497
BEGIN DESCRIPTION:
Bitter Creek Trib14T1 2.0
END DESCRIPTION:
XS GIS Cut Line= 3
      1389804.98      6815888.02      1390155.12      6815578.86
      1390355.01      6815337.99
#Sta/Elev= 30
  4532.9 2477.72  4582.7 2471.24  4625.4 2461.77  4681.4 2450.97  4724.1 2444.97
  4759.7 2435.64  4781.0 2431.96  4823.1 2427.51  4887.2 2422.99  4957.0 2421.64
  4993.5 2419.16  4996.9 2420.42  5007.6 2420.59  5014.1 2419.02  5034.2 2418.28
  5034.5 2417.78  5038.3 2418.28  5041.8 2422.36  5042.8 2423.53  5057.1 2426.06
  5079.1 2427.55  5120.9 2435.75  5143.1 2441.43  5149.6 2441.65  5171.3 2446.45
  5235.0 2457.63  5256.3 2463.56  5305.8 2472.21  5309.5 2474.00  5313.0 2474.10
#Mann=8,-1,0
  4532.9    0.07       0  4823.1   0.035       0  4957.0    0.16       0
  5034.2    0.07       0  5038.3    0.16       0  5041.8    0.07       0
  5171.3    0.16       0  5309.5    0.07       0
Bank Sta=5034.2,5038.3
Exp/Cntr=0.3,0.1

Type RM Length L Ch R = 1,1446,452,452,452
BEGIN DESCRIPTION:
Bitter Creek Trib14T1 1.0
END DESCRIPTION:
XS GIS Cut Line= 3
      1390405.00      6816137.96      1390410.04      6815887.91
      1390455.00      6815488.03
#Sta/Elev= 30
  4749.9 2467.83  4752.4 2467.83  4769.9 2461.91  4789.9 2456.80  4809.9 2450.60
  4839.9 2443.65  4856.1 2438.84  4879.9 2431.08  4909.9 2422.83  4929.9 2419.79
  4959.9 2417.91  4969.9 2417.95  4989.9 2411.85  4994.3 2411.77  4994.6 2411.27
  4998.5 2411.77  5010.0 2413.11  5020.2 2415.79  5040.2 2417.74  5060.3 2417.66
  5080.4 2419.12  5167.6 2420.92  5261.9 2423.15  5281.7 2425.07  5301.8 2428.57
  5321.9 2434.14  5357.4 2445.98  5361.2 2445.83  5372.3 2447.47  5402.4 2450.66
#Mann=9,-1,0
  4749.9    0.07       0  4856.1    0.16       0  4994.3    0.07       0
  4998.5    0.16       0  5020.2    0.07       0  5167.6    0.16       0
  5261.9    0.07       0  5361.2    0.16       0  5372.3    0.07       0
Bank Sta=4994.3,4998.5
Exp/Cntr=0.3,0.1

Type RM Length L Ch R = 1,994,364,364,364
BEGIN DESCRIPTION:
Bitter Creek Trib14T1 0.1
END DESCRIPTION:
XS GIS Cut Line= 3
      1390705.02      6816187.97      1390757.31      6816093.81
      1390655.00      6815688.01
#Sta/Elev= 30
  4892.3 2465.93  4895.1 2465.93  4900.3 2461.52  4906.0 2460.97  4915.1 2456.00
  4922.0 2450.08  4927.7 2447.36  4938.0 2439.87  4943.7 2432.62  4949.5 2430.14
  4972.3 2413.66  4987.2 2410.54  5016.3 2410.04  5025.7 2407.29  5030.8 2409.06
  5034.8 2407.08  5035.1 2406.58  5038.8 2406.58  5039.0 2407.08  5047.2 2413.81
  5057.6 2414.49  5078.2 2413.92  5222.6 2417.96  5231.1 2417.52  5243.2 2418.57
  5263.8 2418.56  5296.6 2419.89  5373.0 2422.75  5400.5 2424.60  5418.5 2427.77
#Mann=5,-1,0
  4892.3    0.07       0  5034.8    0.07       0  5039.0    0.07       0
  5296.6    0.16       0  5373.0    0.07       0
Bank Sta=5034.8,5039
Exp/Cntr=0.3,0.1

Type RM Length L Ch R = 1,630,445,445,445
BEGIN DESCRIPTION:
Bitter Creek Trib14T1 4271
END DESCRIPTION:
XS GIS Cut Line= 3
      1390961.63      6816246.74      1391133.44      6816163.17
      1390770.96      6815602.61
#Sta/Elev= 30
  4734.9 2440.03  4739.2 2440.03  4743.8 2437.95  4749.8 2432.27  4794.5 2414.64
  4811.5 2411.41  4884.7 2409.14  4918.4 2409.68  4944.0 2409.63  4950.3 2407.29
  4956.3 2407.64  4966.3 2405.16  4971.5 2405.88  4990.5 2403.45  4990.7 2402.95
  4994.7 2403.45  5007.7 2406.19  5028.9 2406.12  5038.1 2408.92  5044.0 2407.51
  5059.2 2409.80  5065.1 2408.13  5152.8 2412.87  5238.5 2414.31  5313.1 2416.37
  5412.7 2421.91  5456.1 2425.55  5485.3 2425.74  5579.0 2430.62  5593.5 2432.59
#Mann=7,-1,0
  4734.9    0.07       0  4918.4    0.16       0  4966.3    0.07       0
  4990.5    0.07       0  4994.7    0.07       0  5238.5    0.16       0
  5412.7    0.07       0
Bank Sta=4990.5,4994.7
Exp/Cntr=0.3,0.1

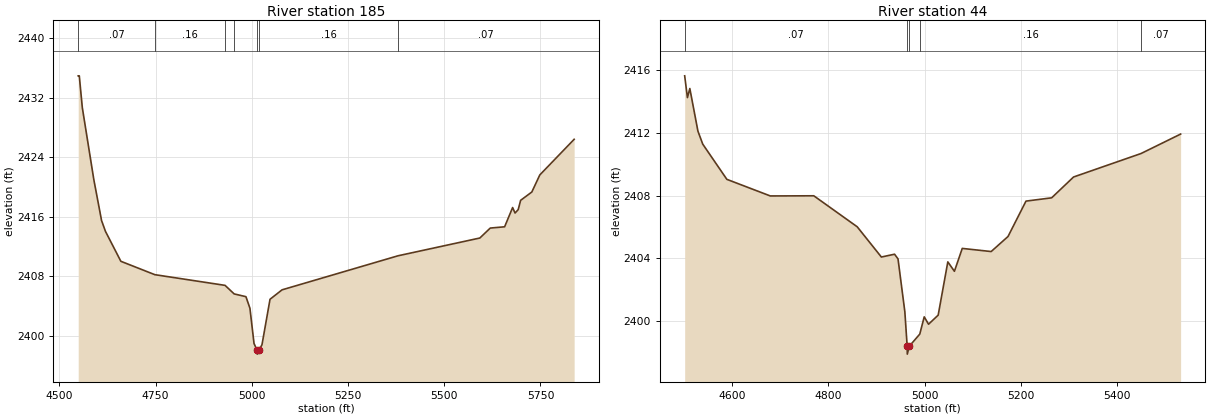
Type RM Length L Ch R = 1,185,141,141,141
BEGIN DESCRIPTION:
Bitter Creek Trib14T1 4272
END DESCRIPTION:
XS GIS Cut Line= 4
      1390974.35      6816291.65      1391375.91      6816270.42
      1391452.11      6816012.35      1390961.63      6815636.89
#Sta/Elev= 30
  4548.7 2434.97  4551.5 2434.97  4559.4 2430.68  4589.4 2420.97  4609.4 2415.50
  4619.5 2414.05  4659.5 2410.02  4747.8 2408.22  4930.4 2406.78  4954.0 2405.63
  4984.6 2405.26  4995.0 2403.70  5005.6 2398.97  5013.7 2398.03  5014.0 2397.53
  5018.0 2398.03  5026.3 2398.79  5047.2 2404.91  5078.5 2406.18  5379.9 2410.76
  5592.5 2413.15  5619.6 2414.49  5656.9 2414.66  5677.7 2417.25  5684.0 2416.51
  5692.2 2416.97  5698.5 2418.22  5727.6 2419.34  5748.4 2421.64  5837.6 2426.43
#Mann=7,-1,0
  4548.7    0.07       0  4747.8    0.16       0  4930.4    0.07       0
  4954.0    0.16       0  5013.7    0.07       0  5018.0    0.16       0
  5379.9    0.07       0
Bank Sta=5013.7,5018
Exp/Cntr=0.3,0.1

Type RM Length L Ch R = 1,44,0,0,0
BEGIN DESCRIPTION:
Bitter Creek Trib14T1 4462
END DESCRIPTION:
XS GIS Cut Line= 6
      1391037.59      6816373.63      1391450.37      6816344.65
      1391511.26      6816286.05      1391507.66      6816113.00
      1391469.23      6816009.22      1391307.39      6815821.64
#Sta/Elev= 30
  4501.7 2415.65  4507.4 2414.26  4512.4 2414.84  4529.2 2412.12  4539.2 2411.29
  4589.3 2409.04  4679.5 2407.98  4769.8 2407.99  4860.0 2406.01  4910.1 2404.08
  4937.5 2404.26  4944.7 2403.96  4958.9 2400.58  4963.7 2398.38  4964.0 2397.88
  4968.0 2398.38  4989.9 2399.16  4999.1 2400.26  5008.1 2399.79  5028.1 2400.37
  5048.1 2403.77  5061.8 2403.17  5078.1 2404.63  5138.1 2404.43  5173.1 2405.39
  5210.4 2407.65  5263.7 2407.86  5309.2 2409.19  5449.4 2410.69  5531.5 2411.93
#Mann=5,-1,0
  4501.7    0.07       0  4963.7    0.07       0  4968.0    0.07       0
  4989.9    0.16       0  5449.4    0.07       0
Bank Sta=4963.7,4968
Exp/Cntr=0.3,0.1

Chan Stop Cuts=-1