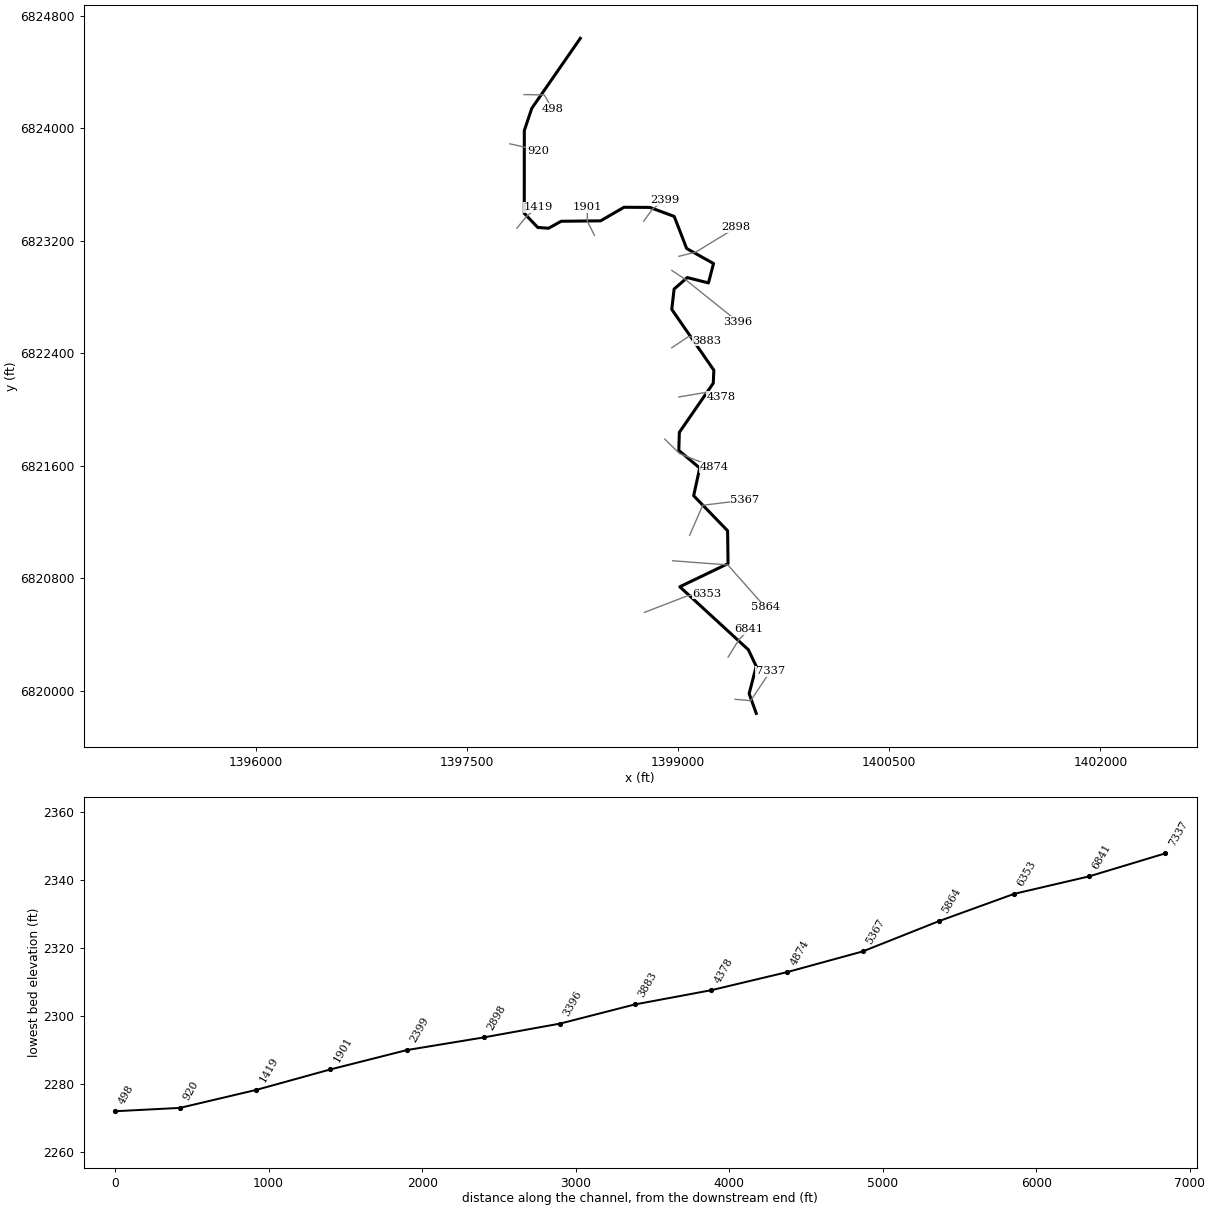
--- Bitter Creek Trib14T2.prj (project) ---

Proj Title=Bitter Creek Trib14T2 Base Level Engineering
Current Plan=p01
Default Exp/Contr=0.3,0.1
English Units
Geom File=g01
Flow File=f01
Plan File=p01
BEGIN DESCRIPTION:
Bitter Creek Trib14T2
END DESCRIPTION:

--- Bitter Creek Trib14T2.p01 (plan) ---

Plan Title=Multiple Run
Short Identifier=Multiple
Geom File=g01
Flow File=f01
Subcritical Flow
K Sum by GR= 0
Std Step Tol= 0.01
Critical Tol= 0.01
Num of Std Step Trials= 20
Max Error Tol= 0.3
Flow Tol Ratio= 0.001
Split Flow NTrial= 30
Split Flow Tol= 0.02
Split Flow Ratio= 0.02
Log Output Level= 0
Friction Slope Method= 1
Unsteady Friction Slope Method= 2
Unsteady Bridges Friction Slope Method= 1
Parabolic Critical Depth
Global Vel Dist=  1 , 1 , 1
Global Log Level= 0
CheckData=True
Encroach Param= -1, 0, 0, 0
BEGIN DESCRIPTION:
Multiple Run
END DESCRIPTION:

--- Bitter Creek Trib14T2.f01 (steady flow) ---

Flow Title=Multiple
Number of Profiles=7
Profile Names=10-year,25-year,50-year,1pct_min,100-year,1pct_plu,500-year
River Rch & RM= Bitter Creek Tri,Reach-1,7337
     597     890    1149     737    1471    2935    2443
Boundary for River Rch & Prof#=Bitter Creek Tri,Reach-1,1
Up Type=0
Dn Type=3
Dn Slope=0.005
Boundary for River Rch & Prof#=Bitter Creek Tri,Reach-1,2
Up Type=0
Dn Type=3
Dn Slope=0.005
Boundary for River Rch & Prof#=Bitter Creek Tri,Reach-1,3
Up Type=0
Dn Type=3
Dn Slope=0.005
Boundary for River Rch & Prof#=Bitter Creek Tri,Reach-1,4
Up Type=0
Dn Type=3
Dn Slope=0.005
Boundary for River Rch & Prof#=Bitter Creek Tri,Reach-1,5
Up Type=0
Dn Type=3
Dn Slope=0.005
Boundary for River Rch & Prof#=Bitter Creek Tri,Reach-1,6
Up Type=0
Dn Type=3
Dn Slope=0.005
Boundary for River Rch & Prof#=Bitter Creek Tri,Reach-1,7
Up Type=0
Dn Type=3
Dn Slope=0.005

--- Bitter Creek Trib14T2.g01 (geometry) ---

Geom Title=Existing Conditions

River Reach=Bitter Creek Tri,Reach-1
Reach XY= 30
      1399555.00      6819838.00      1399504.49      6819978.74
      1399554.92      6820172.61      1399499.17      6820290.30
      1399011.97      6820738.24      1399354.68      6820903.02
      1399351.46      6821136.54      1399110.40      6821385.57
      1399153.34      6821582.56      1399004.89      6821707.89
      1399008.74      6821836.44      1399249.59      6822185.58
      1399253.76      6822278.30      1398954.87      6822710.69
      1398971.41      6822854.80      1399064.63      6822936.91
      1399215.44      6822898.94      1399251.63      6823036.71
      1399060.58      6823143.58      1398972.21      6823371.73
      1398799.06      6823435.74      1398615.50      6823436.80
      1398449.07      6823340.24      1398168.92      6823337.31
      1398080.00      6823287.59      1398002.56      6823293.39
      1397907.05      6823393.84      1397907.38      6823982.47
      1397960.54      6824140.42      1398305.00      6824638.00

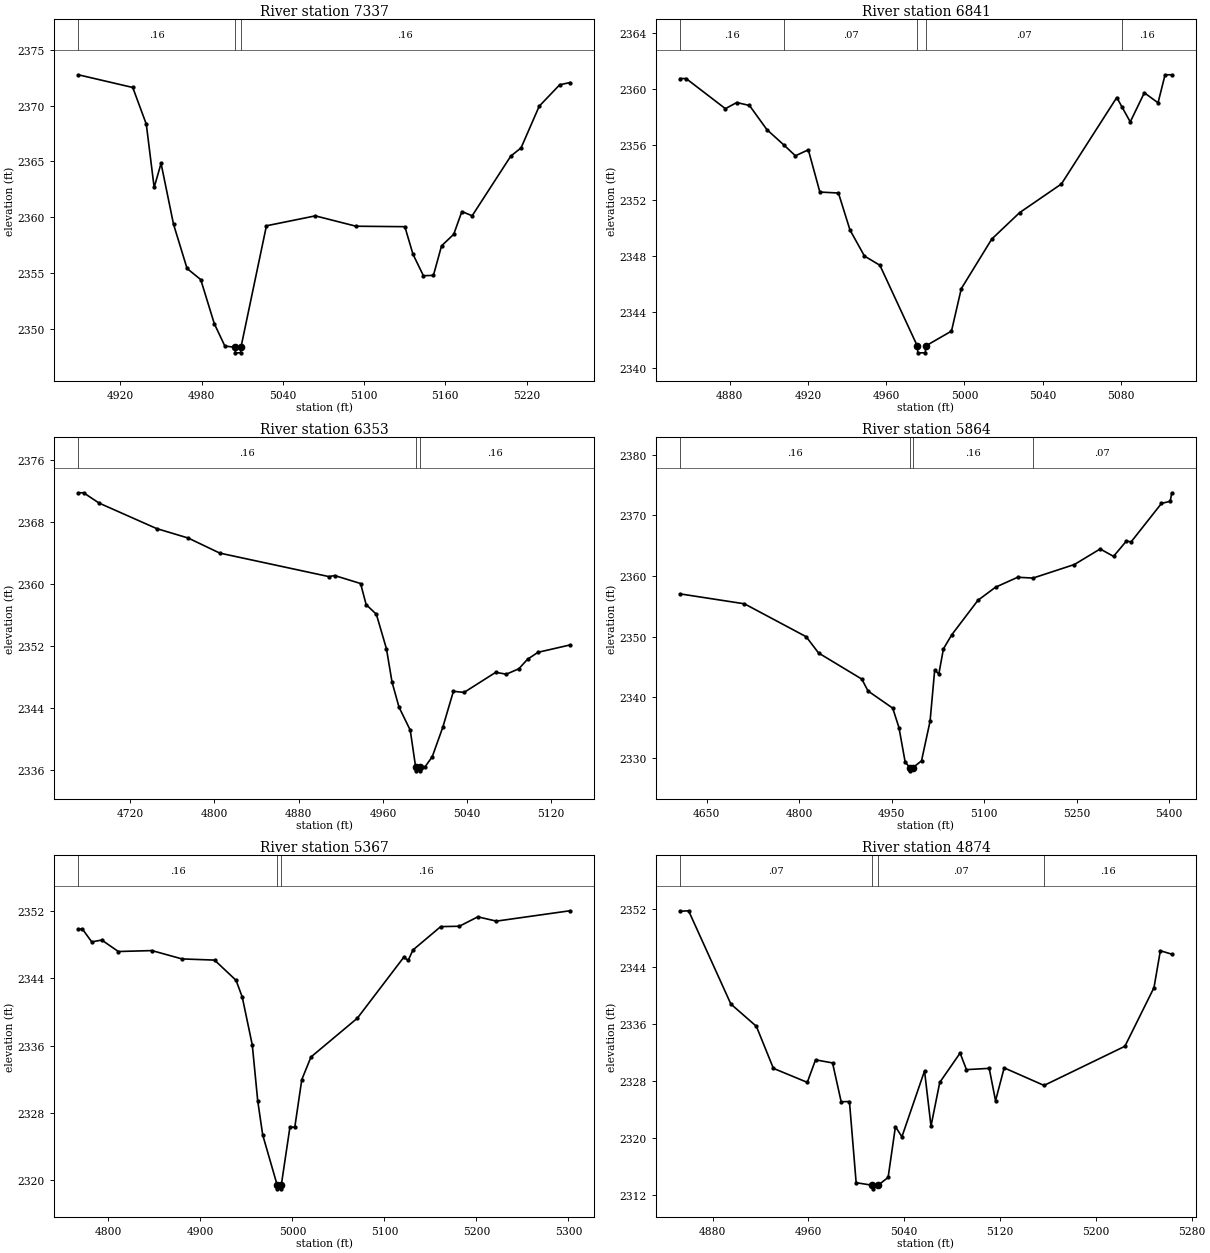
Type RM Length L Ch R = 1,7337,496,496,496
BEGIN DESCRIPTION:
Bitter Creek Trib14T2 14.0
END DESCRIPTION:
XS GIS Cut Line= 3
      1399404.99      6819938.00      1399515.56      6819928.24
      1399655.01      6820138.02
#Sta/Elev= 30
  4889.0 2372.78  4929.2 2371.64  4939.2 2368.35  4945.0 2362.67  4950.1 2364.83
  4959.3 2359.37  4969.3 2355.40  4979.4 2354.40  4989.4 2350.45  4997.2 2348.44
  5004.7 2348.33  5005.0 2347.83  5008.8 2347.83  5009.1 2348.33  5027.9 2359.23
  5064.0 2360.12  5094.1 2359.19  5130.1 2359.15  5136.1 2356.68  5143.8 2354.75
  5151.2 2354.78  5157.2 2357.43  5166.2 2358.47  5172.2 2360.51  5179.8 2360.13
  5208.3 2365.48  5215.9 2366.22  5229.3 2369.96  5244.4 2371.88  5251.9 2372.08
#Mann=3,-1,0
  4889.0    0.16       0  5004.7    0.07       0  5009.1    0.16       0
Bank Sta=5004.7,5009.1
Exp/Cntr=0.3,0.1

Type RM Length L Ch R = 1,6841,488,488,488
BEGIN DESCRIPTION:
Bitter Creek Trib14T2 13.0
END DESCRIPTION:
XS GIS Cut Line= 3
      1399354.99      6820237.98      1399431.73      6820361.36
      1399504.98      6820437.98
#Sta/Elev= 30
  4854.7 2360.74  4857.7 2360.74  4877.8 2358.58  4883.6 2359.02  4890.1 2358.81
  4899.0 2357.08  4907.9 2355.95  4913.6 2355.20  4920.2 2355.63  4926.1 2352.60
  4935.6 2352.53  4941.5 2349.88  4948.9 2348.01  4956.8 2347.35  4975.9 2341.57
  4976.2 2341.07  4980.0 2341.07  4980.3 2341.57  4993.4 2342.63  4998.4 2345.67
  5014.0 2349.23  5028.2 2351.12  5049.6 2353.18  5077.9 2359.38  5080.7 2358.67
  5084.8 2357.63  5092.0 2359.72  5099.0 2359.00  5102.6 2361.01  5106.0 2361.01
#Mann=5,-1,0
  4854.7    0.16       0  4907.9    0.07       0  4975.9    0.07       0
  4980.3    0.07       0  5080.7    0.16       0
Bank Sta=4975.9,4980.3
Exp/Cntr=0.3,0.1

Type RM Length L Ch R = 1,6353,489,489,489
BEGIN DESCRIPTION:
Bitter Creek Trib14T2 12.0
END DESCRIPTION:
XS GIS Cut Line= 3
      1398760.75      6820556.14      1399068.09      6820674.67
      1399205.04      6820688.00
#Sta/Elev= 30
  4670.6 2371.75  4675.6 2371.75  4690.4 2370.42  4745.0 2367.14  4775.0 2365.92
  4805.0 2363.98  4908.8 2360.95  4914.1 2361.09  4938.8 2360.06  4944.1 2357.34
  4953.8 2356.10  4963.4 2351.64  4968.7 2347.35  4975.3 2344.14  4986.0 2341.16
  4991.1 2336.43  4991.4 2335.93  4995.3 2335.93  4995.6 2336.43  5000.0 2336.44
  5006.9 2337.75  5017.0 2341.58  5027.0 2346.18  5037.1 2346.03  5067.2 2348.62
  5077.3 2348.38  5089.2 2349.08  5097.4 2350.30  5107.4 2351.20  5137.6 2352.14
#Mann=3,-1,0
  4670.6    0.16       0  4991.1    0.07       0  4995.6    0.16       0
Bank Sta=4991.1,4995.6
Exp/Cntr=0.3,0.1

Type RM Length L Ch R = 1,5864,497,497,497
BEGIN DESCRIPTION:
Bitter Creek Trib14T2 11.0
END DESCRIPTION:
XS GIS Cut Line= 3
      1398961.14      6820923.18      1399353.03      6820893.65
      1399621.29      6820590.90
#Sta/Elev= 30
  4607.0 2357.05  4711.2 2355.42  4811.4 2350.00  4831.5 2347.32  4901.7 2343.02
  4911.7 2341.07  4951.8 2338.24  4961.9 2335.05  4971.9 2329.42  4979.6 2328.42
  4979.9 2327.92  4984.2 2328.42  4998.5 2329.56  5012.4 2336.09  5019.9 2344.52
  5026.6 2343.86  5034.1 2348.01  5047.6 2350.32  5090.1 2356.00  5118.6 2358.15
  5154.5 2359.79  5179.5 2359.66  5246.6 2361.89  5288.4 2364.45  5310.1 2363.23
  5331.0 2365.76  5338.6 2365.61  5387.9 2371.95  5402.1 2372.30  5404.5 2373.70
#Mann=4,-1,0
  4607.0    0.16       0  4979.6    0.07       0  4984.2    0.16       0
  5179.5    0.07       0
Bank Sta=4979.6,4984.2
Exp/Cntr=0.3,0.1

Type RM Length L Ch R = 1,5367,493,493,493
BEGIN DESCRIPTION:
Bitter Creek Trib14T2 10.0
END DESCRIPTION:
XS GIS Cut Line= 3
      1399081.95      6821104.64      1399174.92      6821317.97
      1399474.26      6821353.98
#Sta/Elev= 30
  4767.3 2349.87  4771.8 2349.87  4781.9 2348.34  4792.8 2348.56  4810.8 2347.20
  4847.3 2347.31  4880.0 2346.32  4915.4 2346.18  4938.8 2343.77  4945.5 2341.78
  4956.4 2336.09  4962.3 2329.46  4967.7 2325.41  4983.3 2319.50  4983.7 2319.00
  4987.7 2319.00  4988.0 2319.50  4997.3 2326.33  5002.6 2326.33  5010.2 2331.98
  5020.2 2334.67  5070.6 2339.28  5120.9 2346.50  5125.9 2346.16  5131.0 2347.38
  5161.2 2350.16  5181.4 2350.20  5201.5 2351.32  5221.7 2350.81  5301.5 2352.04
#Mann=3,-1,0
  4767.3    0.16       0  4983.3    0.07       0  4988.0    0.16       0
Bank Sta=4983.3,4988
Exp/Cntr=0.3,0.1

Type RM Length L Ch R = 1,4874,496,496,496
BEGIN DESCRIPTION:
Bitter Creek Trib14T2 9.0
END DESCRIPTION:
XS GIS Cut Line= 3
      1398905.02      6821787.98      1399010.35      6821685.30
      1399255.01      6821588.00
#Sta/Elev= 30
  4852.9 2351.75  4859.9 2351.82  4895.2 2338.77  4916.5 2335.65  4930.7 2329.77
  4959.0 2327.81  4965.9 2330.96  4980.1 2330.53  4987.3 2325.09  4994.2 2325.13
  4999.8 2313.77  5013.4 2313.41  5013.8 2312.91  5018.1 2313.41  5026.5 2314.51
  5032.6 2321.62  5038.0 2320.19  5056.9 2329.41  5062.3 2321.69  5069.6 2327.80
  5086.6 2331.91  5091.9 2329.59  5110.9 2329.77  5116.2 2325.24  5123.4 2329.84
  5156.7 2327.38  5224.2 2332.86  5248.5 2341.07  5253.8 2346.23  5263.3 2345.75
#Mann=4,-1,0
  4852.9    0.07       0  5013.4    0.07       0  5018.1    0.07       0
  5156.7    0.16       0
Bank Sta=5013.4,5018.1
Exp/Cntr=0.3,0.1

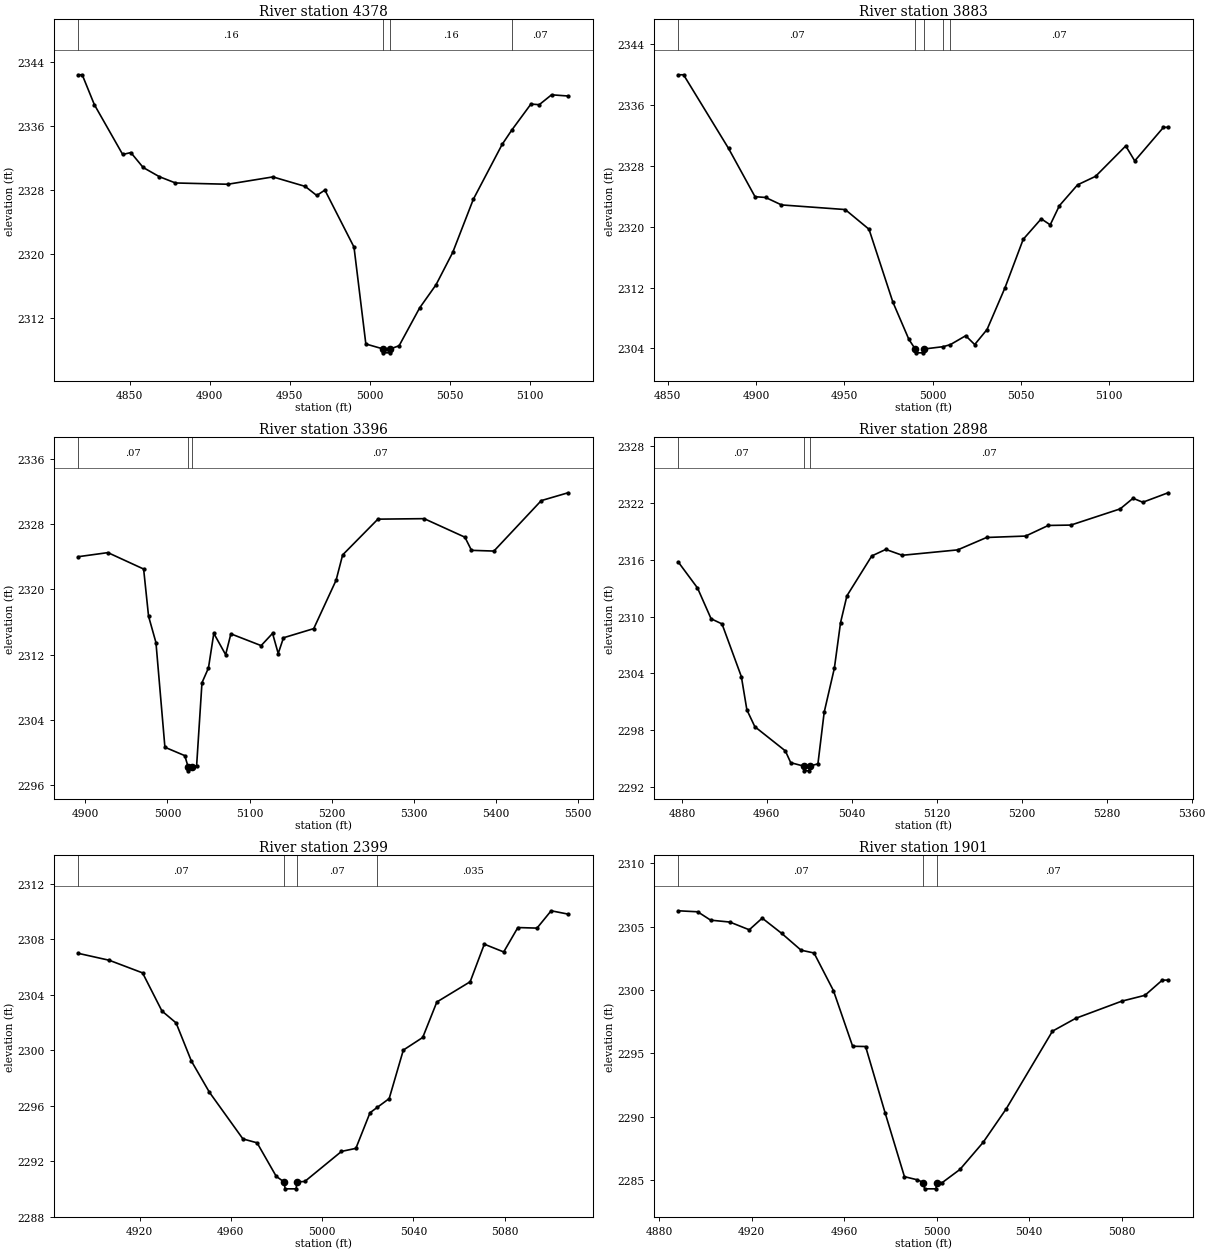
Type RM Length L Ch R = 1,4378,495,495,495
BEGIN DESCRIPTION:
Bitter Creek Trib14T2 8.0
END DESCRIPTION:
XS GIS Cut Line= 3
      1399005.01      6822088.00      1399184.70      6822118.13
      1399304.98      6822088.00
#Sta/Elev= 30
  4817.8 2342.43  4820.3 2342.43  4827.9 2338.68  4845.6 2332.44  4850.7 2332.68
  4858.4 2330.81  4868.5 2329.66  4878.6 2328.87  4911.3 2328.71  4939.5 2329.63
  4959.7 2328.44  4966.9 2327.30  4972.0 2327.98  4990.2 2320.83  4997.6 2308.69
  5008.2 2308.08  5008.6 2307.58  5012.7 2307.58  5013.0 2308.08  5018.4 2308.47
  5031.2 2313.20  5041.5 2316.12  5051.9 2320.16  5064.8 2326.83  5082.8 2333.70
  5088.8 2335.49  5100.8 2338.76  5106.0 2338.68  5113.7 2339.92  5124.0 2339.77
#Mann=4,-1,0
  4817.8    0.16       0  5008.2    0.07       0  5013.0    0.16       0
  5088.8    0.07       0
Bank Sta=5008.2,5013
Exp/Cntr=0.3,0.1

Type RM Length L Ch R = 1,3883,487,487,487
BEGIN DESCRIPTION:
Bitter Creek Trib14T2 7.0
END DESCRIPTION:
XS GIS Cut Line= 3
      1398955.04      6822438.02      1399074.93      6822517.97
      1399205.02      6822488.00
#Sta/Elev= 30
  4855.9 2339.99  4858.9 2339.99  4884.4 2330.30  4899.4 2323.95  4905.4 2323.85
  4914.4 2322.87  4950.5 2322.26  4964.0 2319.67  4977.5 2310.10  4986.6 2305.18
  4990.2 2303.91  4990.5 2303.41  4994.6 2303.41  4995.0 2303.91  5006.0 2304.22
  5010.1 2304.49  5018.8 2305.66  5023.9 2304.50  5030.9 2306.48  5041.1 2311.99
  5051.4 2318.35  5061.6 2321.04  5066.7 2320.25  5071.9 2322.77  5082.2 2325.51
  5092.4 2326.63  5109.5 2330.63  5114.6 2328.66  5130.9 2333.08  5133.5 2333.08
#Mann=5,-1,0
  4855.9    0.07       0  4990.2    0.07       0  4995.0    0.07       0
  5006.0    0.16       0  5010.1    0.07       0
Bank Sta=4990.2,4995
Exp/Cntr=0.3,0.1

Type RM Length L Ch R = 1,3396,498,498,498
BEGIN DESCRIPTION:
Bitter Creek Trib14T2 6.0
END DESCRIPTION:
XS GIS Cut Line= 3
      1398954.97      6822988.02      1399045.19      6822927.57
      1399425.58      6822622.68
#Sta/Elev= 30
  4891.4 2324.01  4927.5 2324.51  4971.0 2322.50  4977.0 2316.72  4986.0 2313.49
  4996.9 2300.67  5021.1 2299.64  5025.1 2298.28  5025.5 2297.78  5029.9 2298.28
  5035.5 2298.41  5042.0 2308.57  5049.9 2310.38  5056.4 2314.62  5070.8 2312.01
  5077.2 2314.56  5114.0 2313.12  5127.9 2314.62  5134.8 2312.15  5141.2 2314.08
  5178.0 2315.20  5205.2 2321.12  5213.2 2324.23  5256.1 2328.61  5312.4 2328.67
  5362.0 2326.40  5370.0 2324.79  5397.3 2324.70  5454.9 2330.88  5487.5 2331.84
#Mann=3,-1,0
  4891.4    0.07       0  5025.1    0.07       0  5029.9    0.07       0
Bank Sta=5025.1,5029.9
Exp/Cntr=0.3,0.1

Type RM Length L Ch R = 1,2898,499,499,499
BEGIN DESCRIPTION:
Bitter Creek Trib14T2 5.0
END DESCRIPTION:
XS GIS Cut Line= 3
      1399005.01      6823088.00      1399124.77      6823117.76
      1399413.13      6823293.70
#Sta/Elev= 30
  4876.6 2315.76  4894.7 2313.02  4907.5 2309.77  4917.8 2309.22  4936.0 2303.66
  4941.2 2300.15  4948.7 2298.37  4977.4 2295.82  4982.5 2294.57  4994.7 2294.21
  4995.1 2293.71  4999.9 2293.71  5000.4 2294.21  5008.1 2294.45  5014.0 2299.90
  5023.6 2304.56  5029.4 2309.36  5035.4 2312.19  5058.8 2316.40  5072.0 2317.09
  5087.5 2316.47  5139.7 2317.04  5166.9 2318.35  5203.7 2318.50  5225.0 2319.62
  5246.3 2319.66  5292.7 2321.37  5304.8 2322.49  5314.0 2322.07  5337.8 2323.07
#Mann=3,-1,0
  4876.6    0.07       0  4994.7    0.07       0  5000.4    0.07       0
Bank Sta=4994.7,5000.4
Exp/Cntr=0.3,0.1

Type RM Length L Ch R = 1,2399,498,498,498
BEGIN DESCRIPTION:
Bitter Creek Trib14T2 4.0
END DESCRIPTION:
XS GIS Cut Line= 3
      1398754.98      6823337.97      1398818.15      6823424.21
      1398905.03      6823488.02
#Sta/Elev= 30
  4893.1 2306.99  4906.7 2306.49  4921.3 2305.58  4929.8 2302.83  4936.0 2301.97
  4942.7 2299.22  4950.6 2296.97  4965.3 2293.60  4971.5 2293.32  4979.9 2290.90
  4983.3 2290.50  4983.8 2290.00  4988.6 2290.00  4989.0 2290.50  4992.4 2290.53
  5008.5 2292.70  5014.8 2292.92  5021.0 2295.49  5024.2 2295.88  5029.4 2296.51
  5035.6 2300.01  5044.1 2300.92  5050.3 2303.48  5064.9 2304.94  5071.1 2307.65
  5079.6 2307.09  5085.8 2308.85  5094.2 2308.81  5100.4 2310.06  5107.8 2309.82
#Mann=4,-1,0
  4893.1    0.07       0  4983.3    0.07       0  4989.0    0.07       0
  5024.2   0.035       0
Bank Sta=4983.3,4989
Exp/Cntr=0.3,0.1

Type RM Length L Ch R = 1,1901,482,482,482
BEGIN DESCRIPTION:
Bitter Creek Trib14T2 3.0
END DESCRIPTION:
XS GIS Cut Line= 3
      1398404.99      6823238.02      1398355.03      6823337.92
      1398355.00      6823438.02
#Sta/Elev= 29
  4888.3 2306.25  4896.7 2306.17  4902.3 2305.51  4910.6 2305.36  4919.0 2304.75
  4924.6 2305.67  4933.0 2304.47  4941.4 2303.14  4947.0 2302.92  4955.4 2299.95
  4963.7 2295.56  4969.3 2295.54  4977.7 2290.33  4986.1 2285.27  4991.7 2285.02
  4994.3 2284.81  4994.8 2284.31  4999.7 2284.31  5000.2 2284.81  5002.5 2284.81
  5010.1 2285.84  5020.1 2287.97  5030.1 2290.62  5050.1 2296.75  5060.1 2297.76
  5080.1 2299.12  5090.1 2299.58  5097.6 2300.78  5100.1 2300.78
#Mann=3,-1,0
  4888.3    0.07       0  4994.3    0.07       0  5000.2    0.07       0
Bank Sta=4994.3,5000.2
Exp/Cntr=0.3,0.1

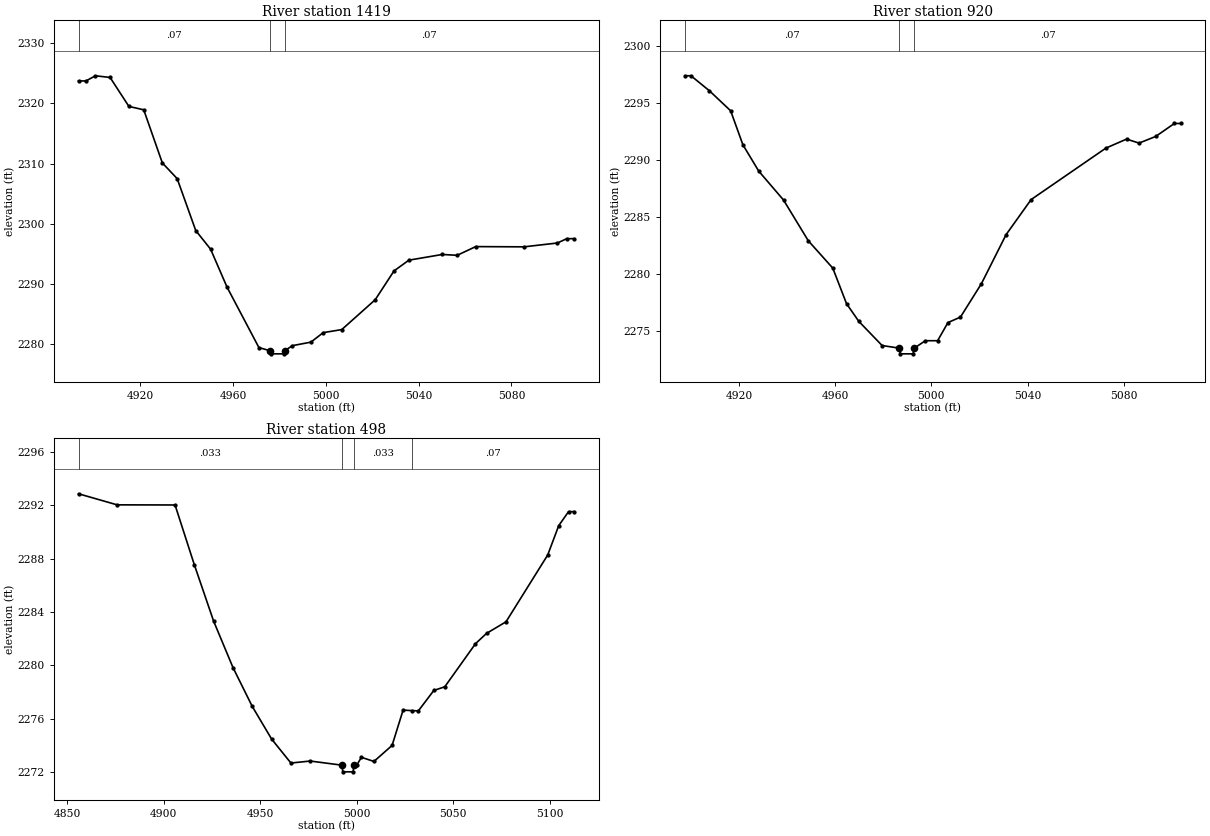
Type RM Length L Ch R = 1,1419,499,499,499
BEGIN DESCRIPTION:
Bitter Creek Trib14T2 2.0
END DESCRIPTION:
XS GIS Cut Line= 3
      1397854.97      6823287.97      1397921.41      6823371.20
      1398005.00      6823438.00
#Sta/Elev= 30
  4893.5 2323.75  4896.7 2323.75  4900.8 2324.61  4907.1 2324.33  4915.2 2319.51
  4921.6 2318.94  4929.6 2310.10  4936.0 2307.48  4944.0 2298.83  4950.4 2295.73
  4957.5 2289.39  4971.2 2279.35  4976.1 2278.80  4976.6 2278.30  4981.8 2278.30
  4982.3 2278.80  4985.6 2279.66  4993.6 2280.25  4998.9 2281.83  5006.9 2282.34
  5021.3 2287.31  5029.4 2292.11  5035.8 2293.90  5050.2 2294.85  5056.6 2294.71
  5064.6 2296.16  5085.4 2296.12  5099.8 2296.76  5103.8 2297.48  5107.0 2297.48
#Mann=3,-1,0
  4893.5    0.07       0  4976.1    0.07       0  4982.3    0.07       0
Bank Sta=4976.1,4982.3
Exp/Cntr=0.3,0.1

Type RM Length L Ch R = 1,920,422,422,422
BEGIN DESCRIPTION:
Bitter Creek Trib14T2 1.0
END DESCRIPTION:
XS GIS Cut Line= 3
      1397805.02      6823888.00      1397904.97      6823865.28
      1398005.02      6823838.00
#Sta/Elev= 29
  4897.5 2297.36  4900.0 2297.36  4907.7 2296.04  4916.5 2294.29  4921.6 2291.31
  4928.2 2289.00  4938.5 2286.47  4948.8 2282.90  4959.0 2280.50  4964.7 2277.39
  4969.8 2275.84  4979.5 2273.72  4986.6 2273.49  4987.1 2272.99  4992.4 2272.99
  4992.9 2273.49  4997.5 2274.14  5002.6 2274.14  5006.9 2275.73  5012.1 2276.21
  5020.8 2279.13  5031.1 2283.44  5041.5 2286.51  5072.6 2291.02  5081.2 2291.81
  5086.4 2291.46  5093.3 2292.04  5101.1 2293.18  5103.7 2293.18
#Mann=3,-1,0
  4897.5    0.07       0  4986.6    0.07       0  4992.9    0.07       0
Bank Sta=4986.6,4992.9
Exp/Cntr=0.3,0.1

Type RM Length L Ch R = 1,498,0,0,0
BEGIN DESCRIPTION:
Bitter Creek Trib14T2 0.1
END DESCRIPTION:
XS GIS Cut Line= 3
      1397905.05      6824238.00      1398049.13      6824235.72
      1398105.02      6824137.97
#Sta/Elev= 30
  4855.9 2292.86  4875.9 2292.03  4905.9 2292.02  4915.9 2287.53  4925.9 2283.30
  4935.9 2279.83  4945.9 2276.91  4955.9 2274.47  4965.9 2272.67  4975.9 2272.82
  4992.3 2272.51  4992.8 2272.01  4998.1 2272.01  4998.6 2272.51  5000.0 2272.51
  5002.4 2273.10  5008.9 2272.79  5018.3 2273.99  5024.0 2276.64  5028.5 2276.60
  5031.9 2276.58  5039.9 2278.11  5045.6 2278.39  5061.5 2281.62  5067.2 2282.39
  5077.3 2283.26  5098.9 2288.27  5104.6 2290.47  5109.7 2291.52  5112.6 2291.52
#Mann=4,-1,0
  4855.9   0.033       0  4992.3   0.033       0  4998.6   0.033       0
  5028.5    0.07       0
Bank Sta=4992.3,4998.6
Exp/Cntr=0.3,0.1

Chan Stop Cuts=-1