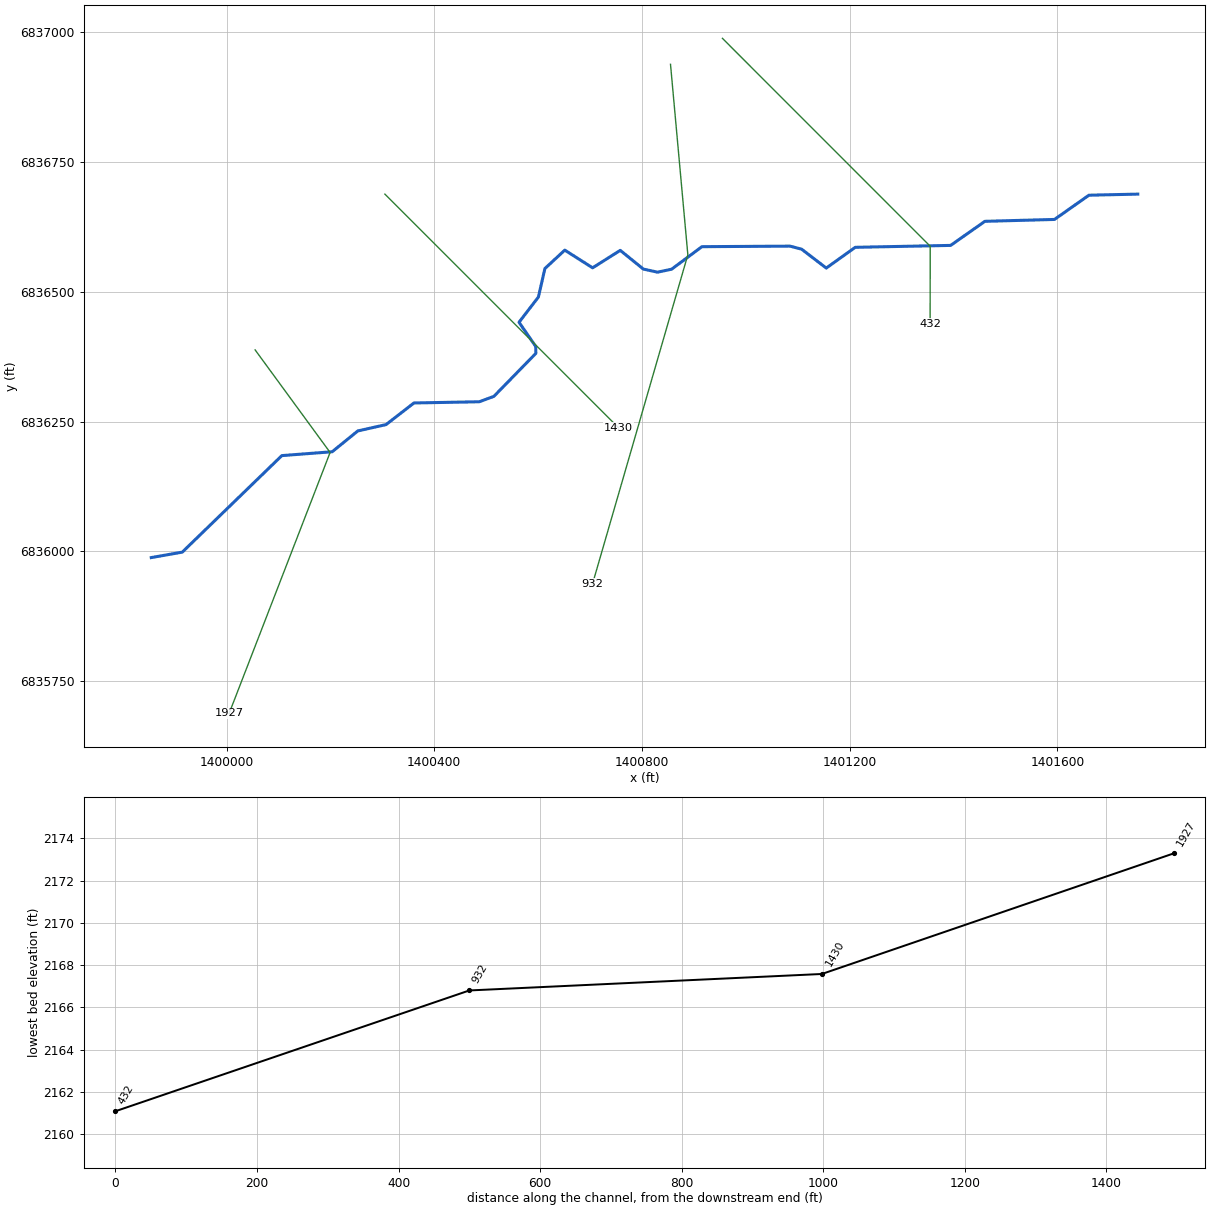
--- Bitter Creek Trib14T3.prj (project) ---

Proj Title=Bitter Creek Trib14T3 Base Level Engineering
Current Plan=p01
Default Exp/Contr=0.3,0.1
English Units
Geom File=g01
Flow File=f01
Plan File=p01
BEGIN DESCRIPTION:
Bitter Creek Trib14T3
END DESCRIPTION:

--- Bitter Creek Trib14T3.p01 (plan) ---

Plan Title=Multiple Run
Short Identifier=Multiple
Geom File=g01
Flow File=f01
Subcritical Flow
K Sum by GR= 0
Std Step Tol= 0.01
Critical Tol= 0.01
Num of Std Step Trials= 20
Max Error Tol= 0.3
Flow Tol Ratio= 0.001
Split Flow NTrial= 30
Split Flow Tol= 0.02
Split Flow Ratio= 0.02
Log Output Level= 0
Friction Slope Method= 1
Unsteady Friction Slope Method= 2
Unsteady Bridges Friction Slope Method= 1
Parabolic Critical Depth
Global Vel Dist=  1 , 1 , 1
Global Log Level= 0
CheckData=True
Encroach Param= -1, 0, 0, 0
BEGIN DESCRIPTION:
Multiple Run
END DESCRIPTION:

--- Bitter Creek Trib14T3.f01 (steady flow) ---

Flow Title=Multiple
Number of Profiles=7
Profile Names=10-year,25-year,50-year,1pct_min,100-year,1pct_plu,500-year
River Rch & RM= Bitter Creek Tri,Reach-1,1927
     290     410     511     316     631    1259     975
Boundary for River Rch & Prof#=Bitter Creek Tri,Reach-1,1
Up Type=0
Dn Type=3
Dn Slope=0.005
Boundary for River Rch & Prof#=Bitter Creek Tri,Reach-1,2
Up Type=0
Dn Type=3
Dn Slope=0.005
Boundary for River Rch & Prof#=Bitter Creek Tri,Reach-1,3
Up Type=0
Dn Type=3
Dn Slope=0.005
Boundary for River Rch & Prof#=Bitter Creek Tri,Reach-1,4
Up Type=0
Dn Type=3
Dn Slope=0.005
Boundary for River Rch & Prof#=Bitter Creek Tri,Reach-1,5
Up Type=0
Dn Type=3
Dn Slope=0.005
Boundary for River Rch & Prof#=Bitter Creek Tri,Reach-1,6
Up Type=0
Dn Type=3
Dn Slope=0.005
Boundary for River Rch & Prof#=Bitter Creek Tri,Reach-1,7
Up Type=0
Dn Type=3
Dn Slope=0.005

--- Bitter Creek Trib14T3.g01 (geometry) ---

Geom Title=Existing Conditions

River Reach=Bitter Creek Tri,Reach-1
Reach XY= 30
      1399855.00      6835988.00      1399914.79      6835998.52
      1400106.50      6836184.39      1400203.41      6836191.83
      1400252.82      6836231.89      1400307.18      6836244.12
      1400360.93      6836285.75      1400486.78      6836288.11
      1400514.85      6836298.48      1400595.71      6836381.31
      1400595.40      6836394.65      1400563.25      6836441.23
      1400600.56      6836489.71      1400613.12      6836544.67
      1400651.42      6836580.12      1400704.98      6836546.04
      1400758.23      6836579.69      1400802.70      6836543.63
      1400829.96      6836537.68      1400857.17      6836543.40
      1400915.50      6836586.76      1401085.01      6836587.82
      1401107.45      6836581.98      1401155.00      6836545.56
      1401210.86      6836585.54      1401394.49      6836589.22
      1401460.53      6836635.61      1401594.50      6836639.21
      1401660.87      6836685.90      1401755.00      6836688.00

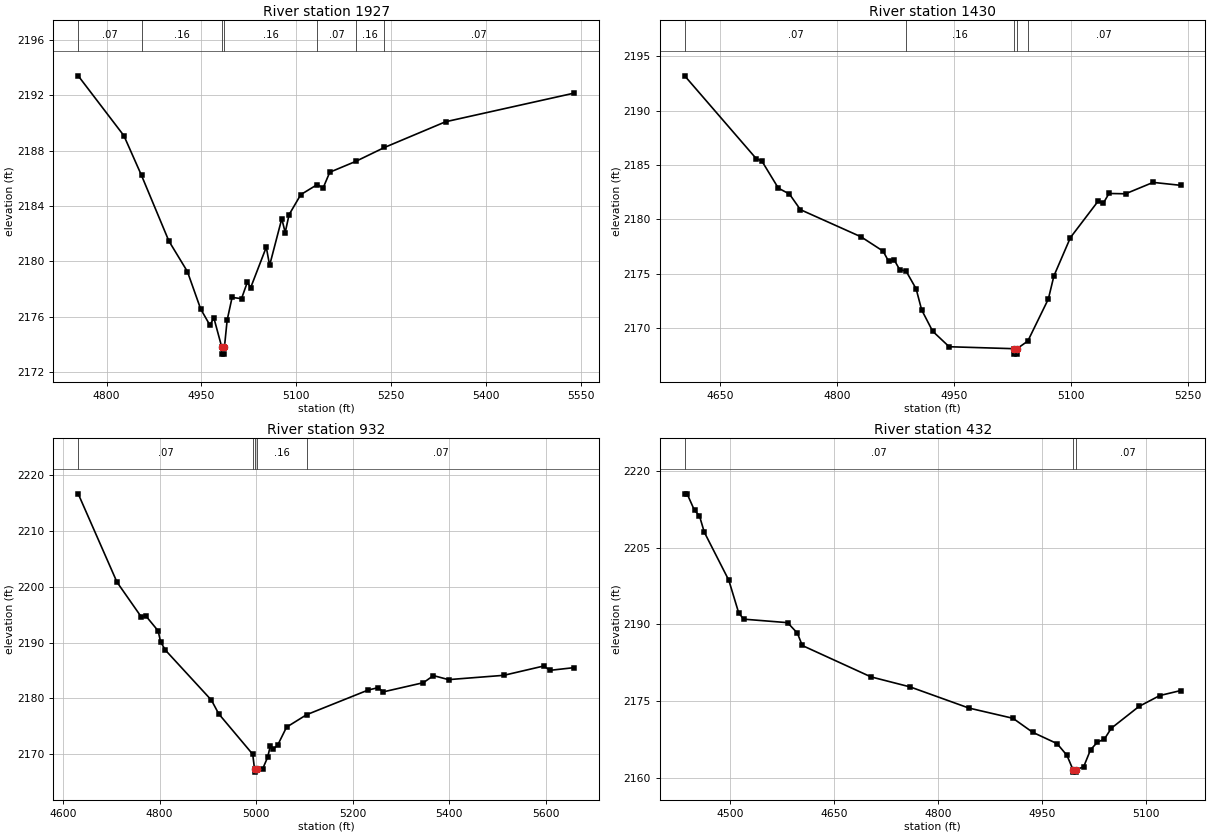
Type RM Length L Ch R = 1,1927,497,497,497
BEGIN DESCRIPTION:
Bitter Creek Trib14T3 3.0
END DESCRIPTION:
XS GIS Cut Line= 3
      1400055.01      6836387.98      1400199.44      6836190.45
      1400004.99      6835687.96
#Sta/Elev= 30
  4755.3 2193.41  4827.5 2189.08  4855.3 2186.21  4898.5 2181.47  4927.8 2179.26
  4948.7 2176.56  4963.4 2175.38  4969.6 2175.91  4982.1 2173.79  4982.4 2173.29
  4986.0 2173.29  4986.3 2173.79  4990.6 2175.75  4998.4 2177.39  5013.3 2177.30
  5022.4 2178.48  5027.8 2178.10  5052.4 2181.02  5057.7 2179.71  5076.9 2183.08
  5082.3 2182.08  5088.4 2183.37  5106.9 2184.82  5133.0 2185.55  5142.2 2185.30
  5152.7 2186.44  5193.5 2187.22  5239.1 2188.23  5335.7 2190.09  5538.8 2192.16
#Mann=7,-1,0
  4755.3    0.07       0  4855.3    0.16       0  4982.1    0.07       0
  4986.3    0.16       0  5133.0    0.07       0  5193.5    0.16       0
  5239.1    0.07       0
Bank Sta=4982.1,4986.3
Exp/Cntr=0.3,0.1

Type RM Length L Ch R = 1,1430,498,498,498
BEGIN DESCRIPTION:
Bitter Creek Trib14T3 2.0
END DESCRIPTION:
XS GIS Cut Line= 3
      1400304.99      6836688.01      1400584.85      6836407.98
      1400754.99      6836238.01
#Sta/Elev= 30
  4604.1 2193.20  4696.0 2185.57  4703.1 2185.36  4724.3 2182.86  4738.5 2182.32
  4752.6 2180.88  4830.4 2178.38  4858.7 2177.06  4865.7 2176.14  4872.8 2176.27
  4879.9 2175.37  4888.3 2175.21  4901.1 2173.59  4908.2 2171.65  4922.3 2169.69
  4943.5 2168.26  5026.2 2168.08  5026.5 2167.58  5030.2 2167.58  5030.5 2168.08
  5044.4 2168.78  5070.8 2172.66  5077.9 2174.78  5099.1 2178.31  5134.4 2181.64
  5141.5 2181.50  5148.6 2182.37  5169.8 2182.34  5205.2 2183.39  5240.5 2183.12
#Mann=5,-1,0
  4604.1    0.07       0  4888.3    0.16       0  5026.2    0.07       0
  5030.5    0.16       0  5044.4    0.07       0
Bank Sta=5026.2,5030.5
Exp/Cntr=0.3,0.1

Type RM Length L Ch R = 1,932,500,500,500
BEGIN DESCRIPTION:
Bitter Creek Trib14T3 1.0
END DESCRIPTION:
XS GIS Cut Line= 3
      1400855.00      6836938.01      1400888.39      6836571.02
      1400704.99      6835937.96
#Sta/Elev= 30
  4631.5 2216.68  4711.8 2200.86  4762.0 2194.64  4772.1 2194.75  4797.1 2192.12
  4802.2 2190.13  4812.3 2188.65  4907.5 2179.70  4922.7 2177.24  4993.1 2170.00
  4996.9 2167.30  4997.2 2166.80  5001.2 2167.30  5013.6 2167.37  5024.0 2169.46
  5029.7 2171.55  5034.9 2170.89  5044.8 2171.64  5063.2 2174.86  5104.7 2177.09
  5232.2 2181.51  5253.0 2181.94  5263.4 2181.18  5346.7 2182.83  5367.5 2184.10
  5398.8 2183.38  5513.3 2184.15  5596.6 2185.83  5608.7 2185.04  5659.1 2185.53
#Mann=5,-1,0
  4631.5    0.07       0  4993.1    0.16       0  4996.9    0.07       0
  5001.2    0.16       0  5104.7    0.07       0
Bank Sta=4996.9,5001.2
Exp/Cntr=0.3,0.1

Type RM Length L Ch R = 1,432,0,0,0
BEGIN DESCRIPTION:
Bitter Creek Trib14T3 0.1
END DESCRIPTION:
XS GIS Cut Line= 3
      1400954.99      6836988.01      1401355.17      6836587.60
      1401355.00      6836438.00
#Sta/Elev= 30
  4433.9 2215.58  4437.4 2215.58  4448.1 2212.32  4455.1 2211.32  4462.2 2208.07
  4497.6 2198.65  4511.7 2192.33  4518.8 2191.04  4582.4 2190.35  4596.5 2188.31
  4603.6 2185.88  4702.6 2179.74  4759.2 2177.77  4844.0 2173.63  4907.7 2171.62
  4936.0 2168.89  4971.3 2166.66  4985.5 2164.38  4994.2 2161.58  4994.5 2161.08
  4998.2 2161.08  4998.5 2161.58  5009.6 2162.10  5019.6 2165.46  5029.6 2166.95
  5039.6 2167.55  5049.6 2169.68  5089.6 2173.95  5119.6 2176.08  5149.6 2177.05
#Mann=3,-1,0
  4433.9    0.07       0  4994.2    0.07       0  4998.5    0.07       0
Bank Sta=4994.2,4998.5
Exp/Cntr=0.3,0.1

Chan Stop Cuts=-1