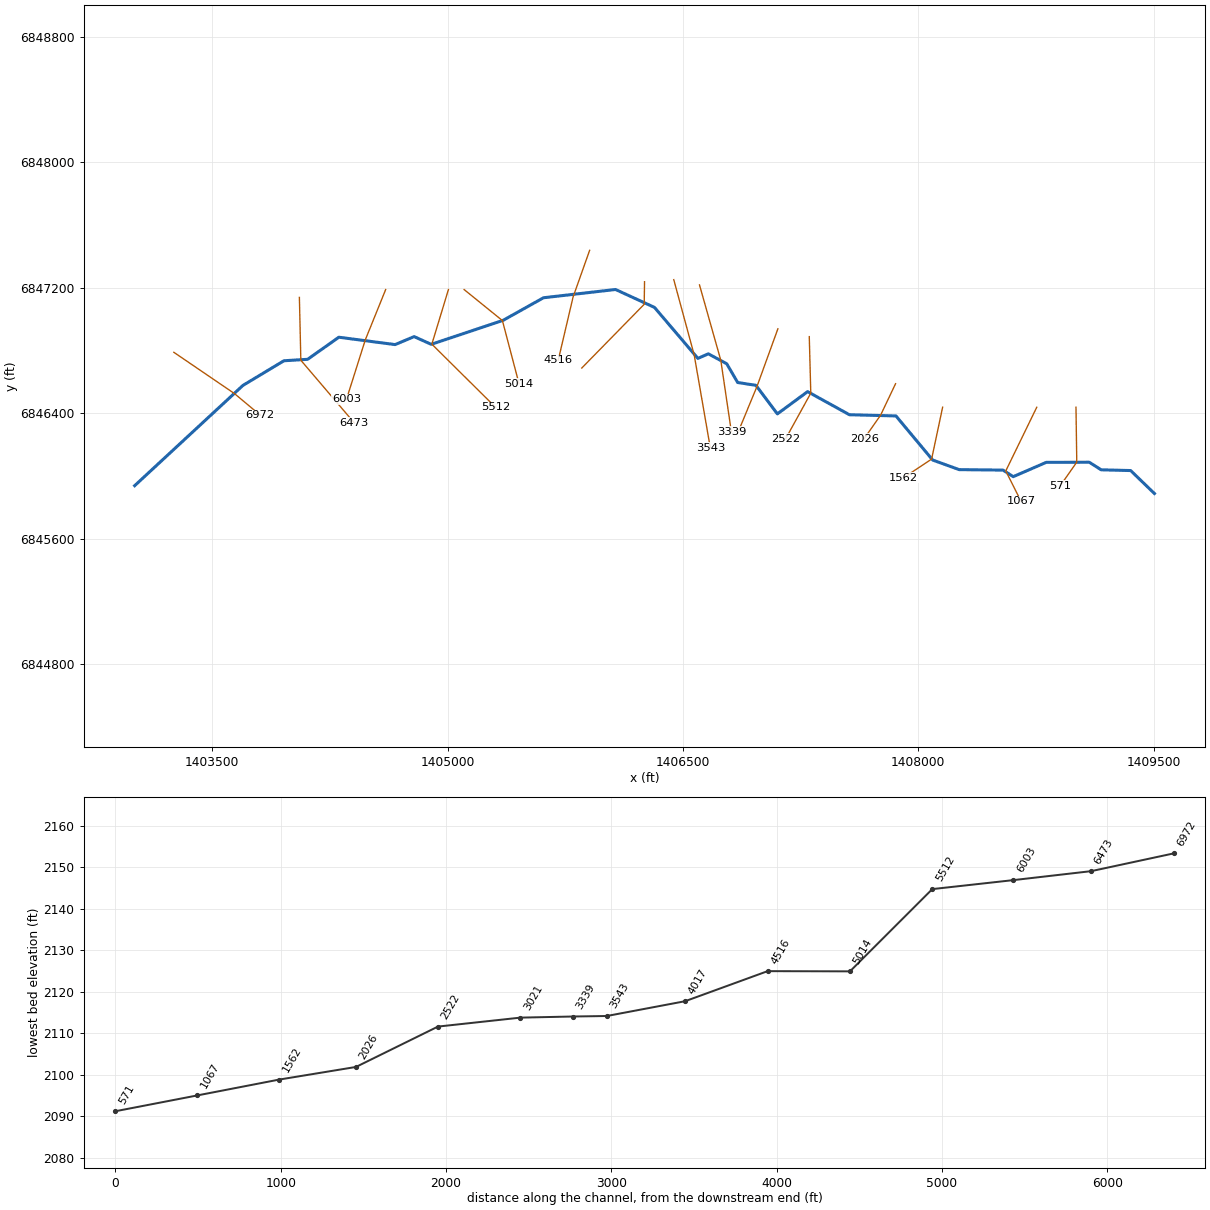
--- Bitter Creek Trib14T4.prj (project) ---

Proj Title=Bitter Creek Trib14T4 Base Level Engineering
Current Plan=p01
Default Exp/Contr=0.3,0.1
English Units
Geom File=g01
Flow File=f01
Plan File=p01
Y Axis Title=Elevation
X Axis Title(PF)=Main Channel Distance
X Axis Title(XS)=Station
BEGIN DESCRIPTION:
Bitter Creek Trib14T4
END DESCRIPTION:
DSS Export Rating Curves= 0
DSS Export Rating Curve Sorted= 0
DSS Export Volume Flow Curves= 0
DXF OffsetX= 0
DXF OffsetY= 0
DXF ScaleX= 1
DXF ScaleY= 10

--- Bitter Creek Trib14T4.p01 (plan) ---

Plan Title=Multiple Run
Short Identifier=Multiple
Geom File=g01
Flow File=f01
Subcritical Flow
K Sum by GR= 0
Std Step Tol= 0.01
Critical Tol= 0.01
Num of Std Step Trials= 20
Max Error Tol= 0.3
Flow Tol Ratio= 0.001
Split Flow NTrial= 30
Split Flow Tol= 0.02
Split Flow Ratio= 0.02
Log Output Level= 0
Friction Slope Method= 1
Unsteady Friction Slope Method= 2
Unsteady Bridges Friction Slope Method= 1
Parabolic Critical Depth
Global Vel Dist=  1 , 1 , 1
Global Log Level= 0
CheckData=True
Encroach Param= -1, 0, 0, 0
BEGIN DESCRIPTION:
Multiple Run
END DESCRIPTION:

--- Bitter Creek Trib14T4.f01 (steady flow) ---

Flow Title=Multiple
Number of Profiles=7
Profile Names=10-year,25-year,50-year,1pct_min,100-year,1pct_plu,500-year
River Rch & RM= Bitter Creek Tri,Reach-1,6972
     507     743     948     601    1199    2392    1944
River Rch & RM= Bitter Creek Tri,Reach-1,1067
     518     759     968     614    1225    2444    1985
Boundary for River Rch & Prof#=Bitter Creek Tri,Reach-1,1
Up Type=0
Dn Type=3
Dn Slope=0.005
Boundary for River Rch & Prof#=Bitter Creek Tri,Reach-1,2
Up Type=0
Dn Type=3
Dn Slope=0.005
Boundary for River Rch & Prof#=Bitter Creek Tri,Reach-1,3
Up Type=0
Dn Type=3
Dn Slope=0.005
Boundary for River Rch & Prof#=Bitter Creek Tri,Reach-1,4
Up Type=0
Dn Type=3
Dn Slope=0.005
Boundary for River Rch & Prof#=Bitter Creek Tri,Reach-1,5
Up Type=0
Dn Type=3
Dn Slope=0.005
Boundary for River Rch & Prof#=Bitter Creek Tri,Reach-1,6
Up Type=0
Dn Type=3
Dn Slope=0.005
Boundary for River Rch & Prof#=Bitter Creek Tri,Reach-1,7
Up Type=0
Dn Type=3
Dn Slope=0.005

--- Bitter Creek Trib14T4.g01 (geometry) ---

Geom Title=Existing Conditions

River Reach=Bitter Creek Tri,Reach-1
Reach XY= 30
      1403005.00      6845938.00      1403695.32      6846577.22
      1403956.56      6846734.24      1404107.44      6846743.48
      1404306.56      6846884.26      1404665.05      6846837.25
      1404786.57      6846888.16      1404895.15      6846838.93
      1405353.42      6846991.83      1405610.93      6847135.76
      1406070.18      6847188.44      1406318.22      6847074.38
      1406595.00      6846749.24      1406661.55      6846778.41
      1406778.83      6846715.15      1406848.55      6846595.75
      1406965.10      6846577.61      1407101.65      6846395.58
      1407294.36      6846537.44      1407560.94      6846390.26
      1407857.45      6846382.54      1408091.67      6846101.39
      1408260.53      6846040.38      1408539.84      6846037.34
      1408605.00      6845995.56      1408815.50      6846086.78
      1409089.78      6846087.48      1409165.51      6846039.22
      1409353.54      6846034.47      1409505.00      6845888.00

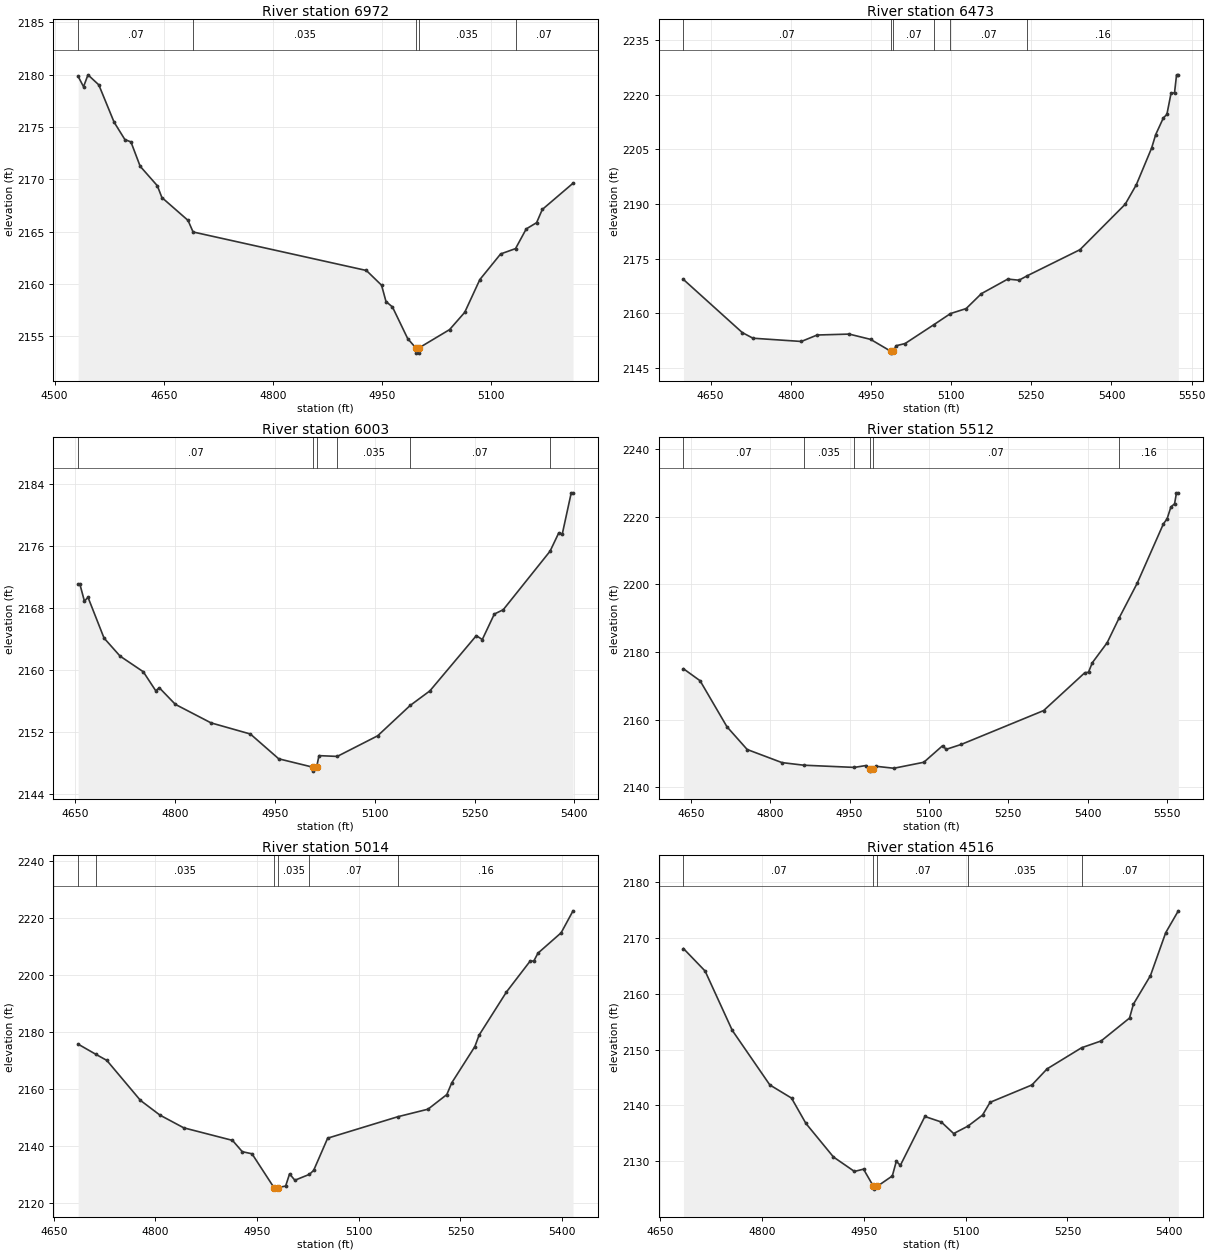
Type RM Length L Ch R = 1,6972,499,499,499
BEGIN DESCRIPTION:
Bitter Creek Trib14T4 13.0
END DESCRIPTION:
XS GIS Cut Line= 3
      1403255.02      6846787.99      1403641.62      6846524.77
      1403805.02      6846387.98
#Sta/Elev= 30
  4532.3 2179.84  4539.7 2178.85  4545.8 2179.99  4560.7 2179.03  4581.7 2175.47
  4596.6 2173.80  4604.9 2173.58  4617.6 2171.25  4641.2 2169.39  4647.5 2168.26
  4683.4 2166.08  4690.4 2164.97  4928.8 2161.29  4949.7 2159.88  4955.8 2158.32
  4964.7 2157.80  4985.7 2154.77  4996.8 2153.89  4997.1 2153.39  5000.9 2153.39
  5001.2 2153.89  5043.3 2155.64  5064.1 2157.29  5084.9 2160.42  5113.5 2162.87
  5134.0 2163.38  5148.7 2165.26  5163.0 2165.86  5170.8 2167.12  5213.1 2169.63
#Mann=5,-1,0
  4532.3    0.07       0  4690.4   0.035       0  4996.8   0.035       0
  5001.2   0.035       0  5134.0    0.07       0
Bank Sta=4996.8,5001.2
Exp/Cntr=0.3,0.1

Type RM Length L Ch R = 1,6473,470,470,470
BEGIN DESCRIPTION:
Bitter Creek Trib14T4 12.0
END DESCRIPTION:
XS GIS Cut Line= 3
      1404055.00      6847138.05      1404064.28      6846737.55
      1404405.00      6846338.01
#Sta/Elev= 30
  4599.4 2169.31  4709.5 2154.74  4729.5 2153.20  4819.9 2152.31  4849.5 2154.08
  4909.5 2154.33  4949.5 2152.88  4987.4 2149.61  4987.7 2149.11  4991.8 2149.61
  4997.3 2151.14  5014.0 2151.74  5067.9 2156.92  5098.9 2159.96  5128.2 2161.33
  5156.7 2165.42  5206.1 2169.42  5227.0 2169.11  5242.9 2170.36  5341.1 2177.48
  5425.7 2189.94  5446.6 2195.32  5475.1 2205.34  5482.8 2209.06  5497.1 2213.63
  5503.7 2214.58  5511.4 2220.33  5518.0 2220.53  5521.8 2225.44  5525.1 2225.44
#Mann=6,-1,0
  4599.4    0.07       0  4987.4    0.07       0  4991.8    0.07       0
  5067.9   0.035       0  5098.9    0.07       0  5242.9    0.16       0
Bank Sta=4987.4,4991.8
Exp/Cntr=0.3,0.1

Type RM Length L Ch R = 1,6003,491,491,491
BEGIN DESCRIPTION:
Bitter Creek Trib14T4 11.0
END DESCRIPTION:
XS GIS Cut Line= 3
      1404605.00      6847188.00      1404475.16      6846867.50
      1404354.99      6846487.97
#Sta/Elev= 30
  4654.2 2171.05  4656.9 2171.05  4663.6 2168.90  4669.0 2169.39  4693.1 2164.13
  4717.2 2161.80  4752.1 2159.78  4770.8 2157.33  4776.2 2157.71  4800.3 2155.57
  4853.9 2153.18  4913.1 2151.74  4955.7 2148.54  5007.4 2147.45  5007.8 2146.95
  5012.6 2147.45  5016.2 2148.95  5043.7 2148.85  5104.4 2151.51  5153.3 2155.43
  5182.9 2157.31  5252.7 2164.44  5261.7 2163.94  5279.8 2167.23  5293.2 2167.79
  5363.6 2175.35  5376.7 2177.72  5381.9 2177.55  5395.4 2182.88  5398.1 2182.88
#Mann=6,-1,0
  4654.2    0.07       0  5007.4    0.07       0  5012.6    0.07       0
  5043.7   0.035       0  5153.3    0.07       0  5363.6    0.16       0
Bank Sta=5007.4,5012.6
Exp/Cntr=0.3,0.1

Type RM Length L Ch R = 1,5512,498,498,498
BEGIN DESCRIPTION:
Bitter Creek Trib14T4 10.0
END DESCRIPTION:
XS GIS Cut Line= 3
      1405005.01      6847188.04      1404899.29      6846839.94
      1405305.00      6846438.00
#Sta/Elev= 30
  4636.2 2175.03  4667.6 2171.49  4718.4 2157.89  4756.6 2151.17  4822.3 2147.30
  4863.5 2146.53  4959.1 2145.88  4981.1 2146.44  4988.9 2145.28  4989.4 2144.78
  4994.2 2145.28  5000.0 2146.21  5033.7 2145.63  5090.3 2147.40  5125.6 2152.27
  5132.7 2151.23  5161.0 2152.67  5316.6 2162.67  5394.3 2173.84  5401.4 2174.01
  5408.5 2176.78  5436.7 2182.74  5459.1 2189.98  5493.3 2200.27  5542.9 2217.84
  5549.9 2219.33  5557.0 2222.81  5564.0 2223.78  5567.6 2227.01  5571.1 2227.01
#Mann=6,-1,0
  4636.2    0.07       0  4863.5   0.035       0  4959.1    0.07       0
  4988.9    0.07       0  4994.2    0.07       0  5459.1    0.16       0
Bank Sta=4988.9,4994.2
Exp/Cntr=0.3,0.1

Type RM Length L Ch R = 1,5014,498,498,498
BEGIN DESCRIPTION:
Bitter Creek Trib14T4 9.0
END DESCRIPTION:
XS GIS Cut Line= 3
      1405105.04      6847187.97      1405349.03      6846990.33
      1405455.01      6846587.95
#Sta/Elev= 30
  4686.0 2175.83  4712.1 2172.27  4728.3 2170.13  4777.9 2156.09  4806.7 2150.92
  4841.8 2146.46  4913.7 2142.05  4928.1 2138.09  4942.5 2137.34  4975.0 2125.44
  4975.4 2124.94  4980.4 2125.44  4992.1 2126.03  4997.9 2130.30  5005.7 2128.06
  5027.2 2130.13  5033.4 2131.51  5054.1 2142.83  5157.8 2150.37  5202.1 2153.00
  5229.9 2158.14  5237.2 2162.27  5271.3 2175.01  5277.5 2179.00  5317.9 2194.16
  5353.0 2205.05  5358.2 2204.99  5364.3 2207.77  5398.5 2214.92  5416.1 2222.64
#Mann=6,-1,0
  4686.0    0.07       0  4712.1   0.035       0  4975.0   0.035       0
  4980.4   0.035       0  5027.2    0.07       0  5157.8    0.16       0
Bank Sta=4975,4980.4
Exp/Cntr=0.3,0.1

Type RM Length L Ch R = 1,4516,499,499,499
BEGIN DESCRIPTION:
Bitter Creek Trib14T4 8.0
END DESCRIPTION:
XS GIS Cut Line= 3
      1405905.01      6847438.02      1405799.47      6847140.38
      1405705.00      6846738.02
#Sta/Elev= 30
  4684.2 2168.11  4716.1 2164.08  4756.1 2153.45  4811.5 2143.66  4843.4 2141.31
  4864.6 2136.77  4905.2 2130.75  4936.1 2128.16  4949.5 2128.57  4964.1 2125.49
  4964.6 2124.99  4969.7 2125.49  4991.9 2127.35  4997.8 2129.97  5003.8 2129.26
  5039.9 2138.01  5064.1 2137.02  5082.3 2134.95  5103.3 2136.28  5124.8 2138.26
  5136.0 2140.55  5197.6 2143.66  5219.9 2146.54  5270.8 2150.33  5299.6 2151.55
  5341.4 2155.65  5347.1 2158.14  5372.2 2163.25  5394.7 2170.95  5413.3 2174.87
#Mann=5,-1,0
  4684.2    0.07       0  4964.1    0.07       0  4969.7    0.07       0
  5103.3   0.035       0  5270.8    0.07       0
Bank Sta=4964.1,4969.7
Exp/Cntr=0.3,0.1

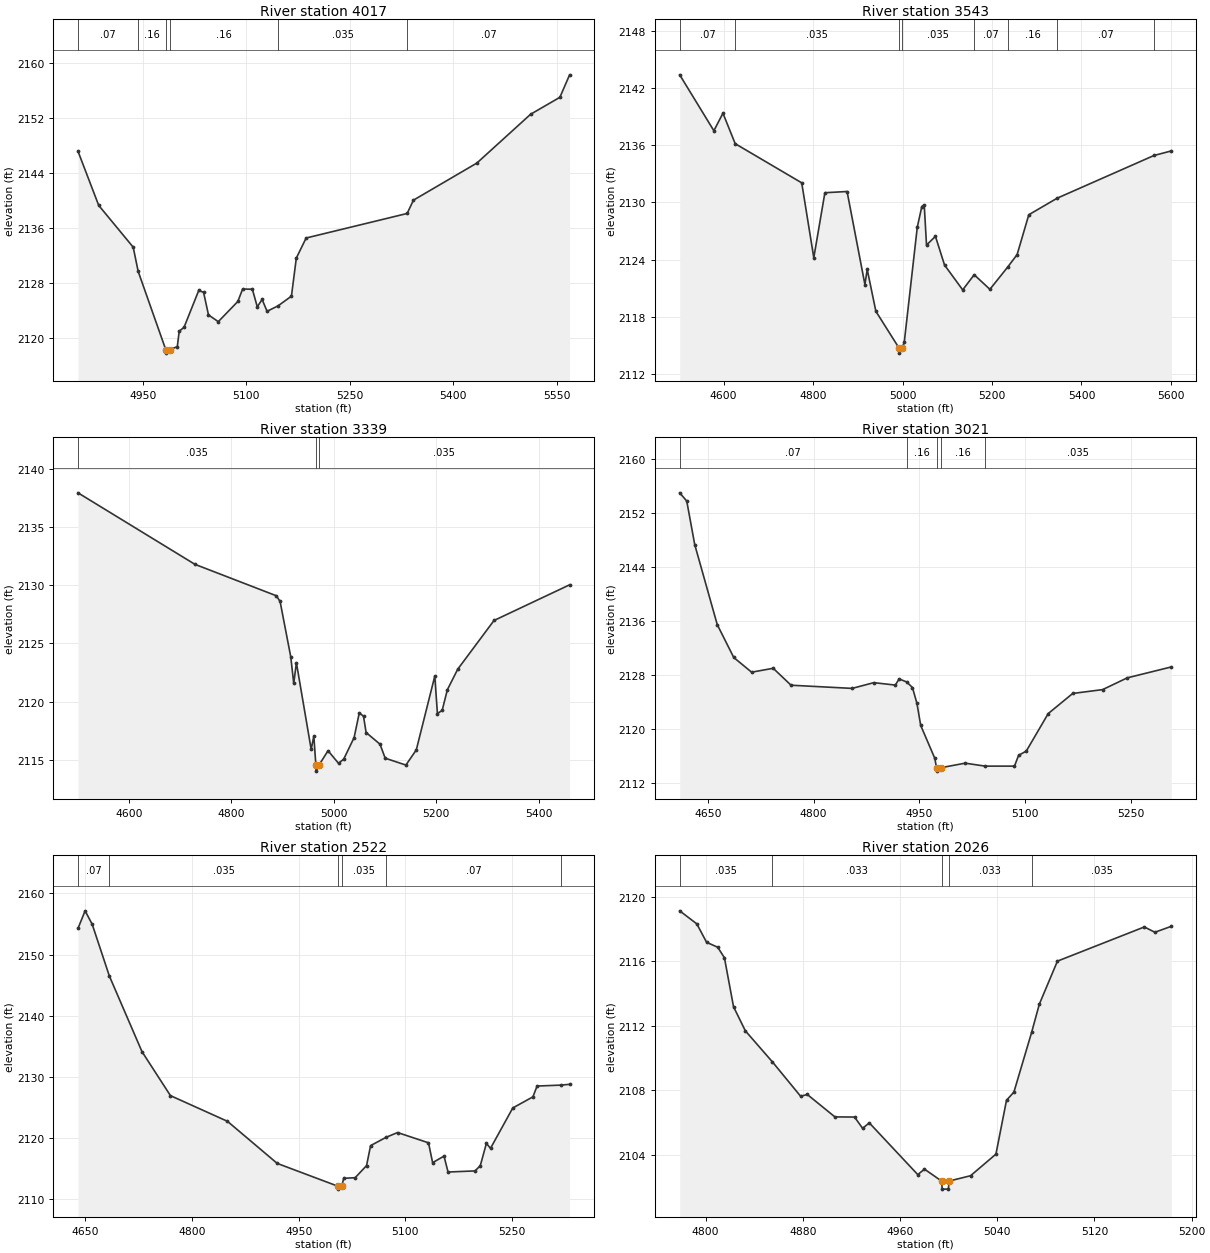
Type RM Length L Ch R = 1,4017,474,474,474
BEGIN DESCRIPTION:
Bitter Creek Trib14T4 7.0
END DESCRIPTION:
XS GIS Cut Line= 3
      1406255.00      6847237.99      1406252.81      6847094.10
      1405854.99      6846687.99
#Sta/Elev= 30
  4856.1 2147.18  4886.1 2139.29  4936.1 2133.19  4943.3 2129.66  4983.3 2118.24
  4983.8 2117.74  4989.0 2118.24  5000.0 2118.69  5002.8 2120.94  5009.8 2121.51
  5031.1 2126.89  5038.1 2126.60  5045.2 2123.31  5059.4 2122.33  5087.7 2125.27
  5094.7 2127.09  5108.8 2127.06  5115.9 2124.49  5122.9 2125.57  5130.1 2123.84
  5146.1 2124.64  5165.4 2126.05  5172.5 2131.61  5186.7 2134.53  5333.1 2138.11
  5342.2 2140.05  5434.1 2145.46  5512.0 2152.58  5554.4 2155.05  5568.5 2158.33
#Mann=6,-1,0
  4856.1    0.07       0  4943.3    0.16       0  4983.3    0.07       0
  4989.0    0.16       0  5146.1   0.035       0  5333.1    0.07       0
Bank Sta=4983.3,4989
Exp/Cntr=0.3,0.1

Type RM Length L Ch R = 1,3543,204,204,204
BEGIN DESCRIPTION:
Bitter Creek Trib14T4 6.0
END DESCRIPTION:
XS GIS Cut Line= 3
      1406441.26      6847251.31      1406571.66      6846770.48
      1406674.34      6846178.41
#Sta/Elev= 30
  4501.8 2143.39  4578.2 2137.52  4598.5 2139.36  4625.9 2136.16  4774.6 2132.05
  4801.6 2124.19  4826.4 2131.01  4876.0 2131.14  4915.9 2121.37  4921.0 2122.96
  4940.4 2118.56  4992.6 2114.67  4993.1 2114.17  4998.4 2114.67  5003.8 2115.29
  5033.0 2127.40  5043.1 2129.56  5048.5 2129.74  5053.6 2125.52  5073.6 2126.43
  5093.9 2123.42  5134.5 2120.81  5160.2 2122.40  5195.3 2120.87  5235.2 2123.21
  5256.2 2124.52  5282.3 2128.70  5345.8 2130.44  5562.1 2134.92  5600.9 2135.40
#Mann=8,-1,0
  4501.8    0.07       0  4625.9   0.035       0  4992.6   0.035       0
  4998.4   0.035       0  5160.2    0.07       0  5235.2    0.16       0
  5345.8    0.07       0  5562.1   0.063       0
Bank Sta=4992.6,4998.4
Exp/Cntr=0.3,0.1

Type RM Length L Ch R = 1,3339,318,318,318
BEGIN DESCRIPTION:
Bitter Creek Trib14T4 4173
END DESCRIPTION:
XS GIS Cut Line= 3
      1406605.34      6847217.42      1406741.07      6846737.13
      1406808.33      6846282.08
#Sta/Elev= 30
  4500.9 2137.92  4728.9 2131.79  4887.9 2129.09  4895.2 2128.60  4916.0 2123.85
  4921.8 2121.57  4927.0 2123.35  4955.8 2115.92  4961.0 2117.05  4965.0 2114.55
  4965.5 2114.05  4970.8 2114.55  4988.7 2115.80  5009.2 2114.72  5019.3 2115.08
  5039.6 2116.93  5049.7 2119.05  5057.9 2118.76  5063.0 2117.36  5090.1 2116.36
  5100.2 2115.16  5140.6 2114.57  5160.9 2115.87  5197.0 2122.20  5202.1 2118.99
  5211.4 2119.26  5221.5 2121.03  5241.7 2122.79  5312.5 2126.97  5460.0 2130.03
#Mann=3,-1,0
  4500.9   0.035       0  4965.0   0.035       0  4970.8   0.035       0
Bank Sta=4965,4970.8
Exp/Cntr=0.3,0.1

Type RM Length L Ch R = 1,3021,499,499,499
BEGIN DESCRIPTION:
Bitter Creek Trib14T4 5.0
END DESCRIPTION:
XS GIS Cut Line= 3
      1407105.01      6846938.04      1406972.13      6846571.70
      1406855.01      6846288.02
#Sta/Elev= 30
  4610.3 2155.02  4620.3 2153.80  4631.6 2147.35  4663.5 2135.49  4686.9 2130.62
  4712.2 2128.44  4742.8 2129.02  4768.1 2126.51  4854.6 2126.04  4885.3 2126.89
  4915.9 2126.53  4921.2 2127.45  4931.9 2126.99  4940.1 2126.17  4946.5 2123.81
  4951.8 2120.55  4971.8 2115.67  4974.2 2114.28  4974.6 2113.78  4980.1 2114.28
  5014.8 2114.96  5043.1 2114.52  5084.7 2114.52  5090.5 2116.12  5101.4 2116.75
  5132.5 2122.31  5167.2 2125.29  5209.6 2125.86  5244.4 2127.60  5306.9 2129.22
#Mann=5,-1,0
  4610.3    0.07       0  4931.9    0.16       0  4974.2    0.07       0
  4980.1    0.16       0  5043.1   0.035       0
Bank Sta=4974.2,4980.1
Exp/Cntr=0.3,0.1

Type RM Length L Ch R = 1,2522,496,496,496
BEGIN DESCRIPTION:
Bitter Creek Trib14T4 4.0
END DESCRIPTION:
XS GIS Cut Line= 3
      1407305.00      6846887.98      1407314.67      6846527.80
      1407154.99      6846237.98
#Sta/Elev= 30
  4639.7 2154.28  4649.7 2157.16  4659.7 2154.95  4683.8 2146.49  4729.7 2134.11
  4769.7 2126.92  4849.8 2122.72  4919.8 2115.83  5004.6 2112.12  5005.1 2111.62
  5010.6 2112.12  5013.3 2113.39  5029.4 2113.49  5045.4 2115.47  5051.1 2118.74
  5072.9 2120.10  5089.0 2120.88  5132.5 2119.20  5138.3 2115.95  5154.3 2117.02
  5160.0 2114.42  5197.9 2114.60  5205.3 2115.45  5213.9 2119.10  5219.7 2118.30
  5251.0 2124.90  5279.3 2126.72  5285.2 2128.49  5318.8 2128.64  5330.9 2128.77
#Mann=6,-1,0
  4639.7    0.07       0  4683.8   0.035       0  5004.6   0.035       0
  5010.6   0.035       0  5072.9    0.07       0  5318.8   0.035       0
Bank Sta=5004.6,5010.6
Exp/Cntr=0.3,0.1

Type RM Length L Ch R = 1,2026,464,464,464
BEGIN DESCRIPTION:
Bitter Creek Trib14T4 3.0
END DESCRIPTION:
XS GIS Cut Line= 3
      1407855.00      6846587.99      1407760.04      6846388.10
      1407655.00      6846238.00
#Sta/Elev= 30
  4778.7 2119.14  4792.8 2118.33  4800.8 2117.19  4810.0 2116.88  4815.5 2116.23
  4823.0 2113.19  4832.7 2111.70  4855.0 2109.77  4878.2 2107.64  4883.7 2107.75
  4906.4 2106.36  4922.6 2106.35  4929.2 2105.65  4934.7 2105.99  4974.6 2102.78
  4980.1 2103.12  4994.2 2102.38  4994.7 2101.88  4999.8 2101.88  5000.3 2102.38
  5018.0 2102.71  5038.9 2104.05  5047.6 2107.39  5053.7 2107.90  5068.3 2111.61
  5074.6 2113.35  5089.5 2116.02  5161.0 2118.14  5169.7 2117.81  5183.2 2118.18
#Mann=5,-1,0
  4778.7   0.035       0  4855.0   0.033       0  4994.2   0.033       0
  5000.3   0.033       0  5068.3   0.035       0
Bank Sta=4994.2,5000.3
Exp/Cntr=0.3,0.1

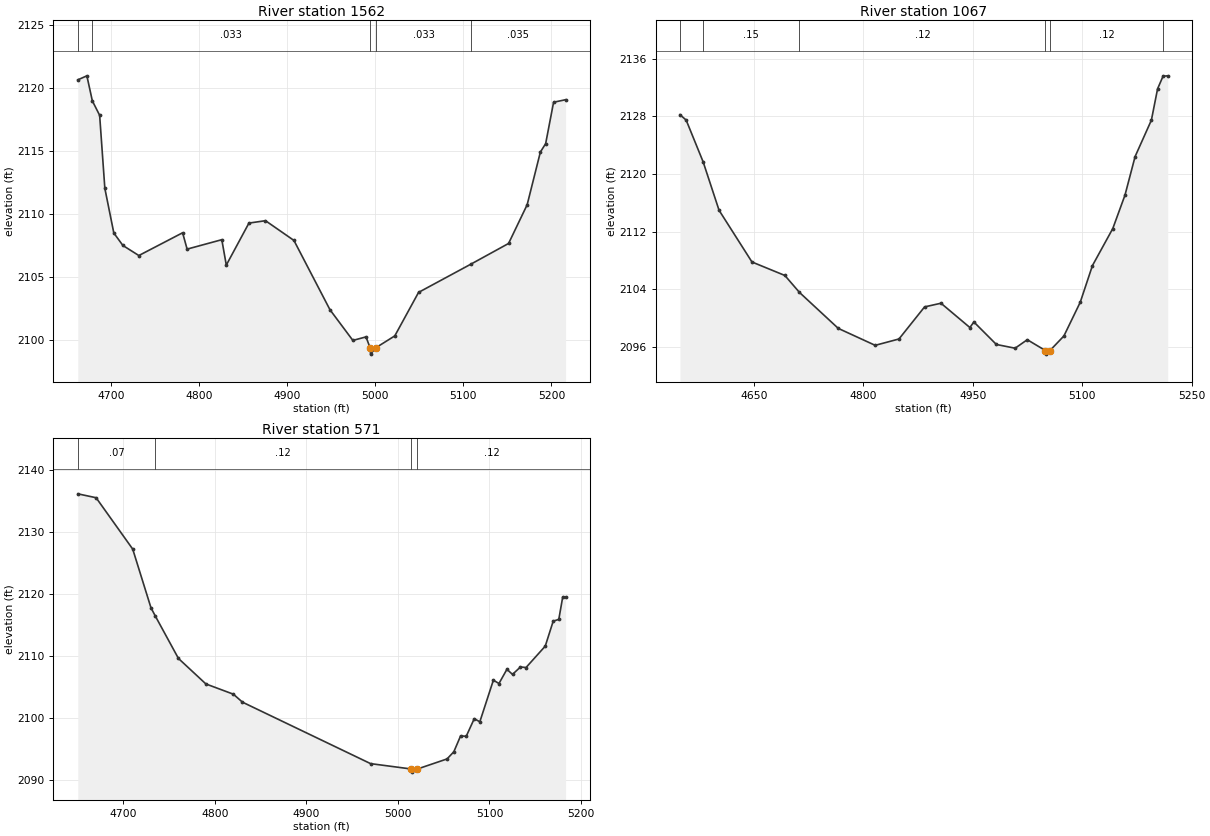
Type RM Length L Ch R = 1,1562,495,495,495
BEGIN DESCRIPTION:
Bitter Creek Trib14T4 2.0
END DESCRIPTION:
XS GIS Cut Line= 3
      1408155.01      6846438.03      1408084.80      6846107.61
      1407904.96      6845987.97
#Sta/Elev= 30
  4662.2 2120.65  4672.5 2120.97  4678.7 2118.98  4687.0 2117.83  4692.9 2112.02
  4703.1 2108.47  4713.4 2107.48  4731.5 2106.68  4781.2 2108.49  4786.3 2107.19
  4825.7 2107.94  4830.8 2105.92  4856.5 2109.26  4875.3 2109.45  4907.6 2107.88
  4948.5 2102.37  4974.5 2099.93  4989.4 2100.21  4994.1 2099.34  4994.6 2098.84
  5000.4 2099.34  5022.1 2100.29  5049.1 2103.75  5108.9 2106.01  5151.3 2107.64
  5172.4 2110.72  5187.4 2114.91  5193.4 2115.58  5202.4 2118.87  5216.0 2119.07
#Mann=5,-1,0
  4662.2   0.035       0  4678.7   0.033       0  4994.1   0.033       0
  5000.4   0.033       0  5108.9   0.035       0
Bank Sta=4994.1,5000.4
Exp/Cntr=0.3,0.1

Type RM Length L Ch R = 1,1067,496,496,496
BEGIN DESCRIPTION:
Bitter Creek Trib14T4 1.0
END DESCRIPTION:
XS GIS Cut Line= 3
      1408754.99      6846437.97      1408557.45      6846031.98
      1408654.99      6845838.03
#Sta/Elev= 30
  4548.5 2128.23  4557.0 2127.48  4580.3 2121.68  4602.1 2114.97  4647.2 2107.80
  4692.3 2105.93  4712.3 2103.58  4765.5 2098.59  4816.1 2096.24  4848.7 2097.12
  4883.8 2101.57  4906.3 2102.08  4945.9 2098.71  4951.4 2099.48  4982.2 2096.36
  5007.9 2095.84  5024.6 2097.02  5049.4 2095.52  5049.9 2095.02  5055.7 2095.52
  5074.8 2097.54  5097.2 2102.22  5113.9 2107.30  5141.8 2112.44  5158.5 2117.07
  5172.4 2122.43  5194.7 2127.47  5203.2 2131.82  5210.7 2133.57  5217.1 2133.62
#Mann=6,-1,0
  4548.5    0.16       0  4580.3    0.15       0  4712.3    0.12       0
  5049.4    0.07       0  5055.7    0.12       0  5210.7   0.035       0
Bank Sta=5049.4,5055.7
Exp/Cntr=0.3,0.1

Type RM Length L Ch R = 1,571,0,0,0
BEGIN DESCRIPTION:
Bitter Creek Trib14T4 0.1
END DESCRIPTION:
XS GIS Cut Line= 3
      1409005.00      6846437.96      1409010.04      6846088.09
      1408905.00      6845938.00
#Sta/Elev= 30
  4650.1 2136.08  4670.1 2135.45  4710.1 2127.17  4730.1 2117.69  4734.6 2116.43
  4760.1 2109.53  4790.1 2105.42  4820.1 2103.77  4830.1 2102.48  4970.1 2092.57
  5014.8 2091.70  5015.3 2091.20  5021.2 2091.70  5053.7 2093.33  5061.1 2094.49
  5068.5 2097.05  5074.6 2096.97  5083.4 2099.82  5089.5 2099.32  5104.3 2106.03
  5110.4 2105.49  5119.1 2107.78  5125.2 2106.96  5133.9 2108.16  5140.0 2108.07
  5161.0 2111.52  5169.7 2115.55  5175.8 2115.83  5180.1 2119.45  5183.2 2119.45
#Mann=4,-1,0
  4650.1    0.07       0  4734.6    0.12       0  5014.8    0.07       0
  5021.2    0.12       0
Bank Sta=5014.8,5021.2
Exp/Cntr=0.3,0.1

Chan Stop Cuts=-1