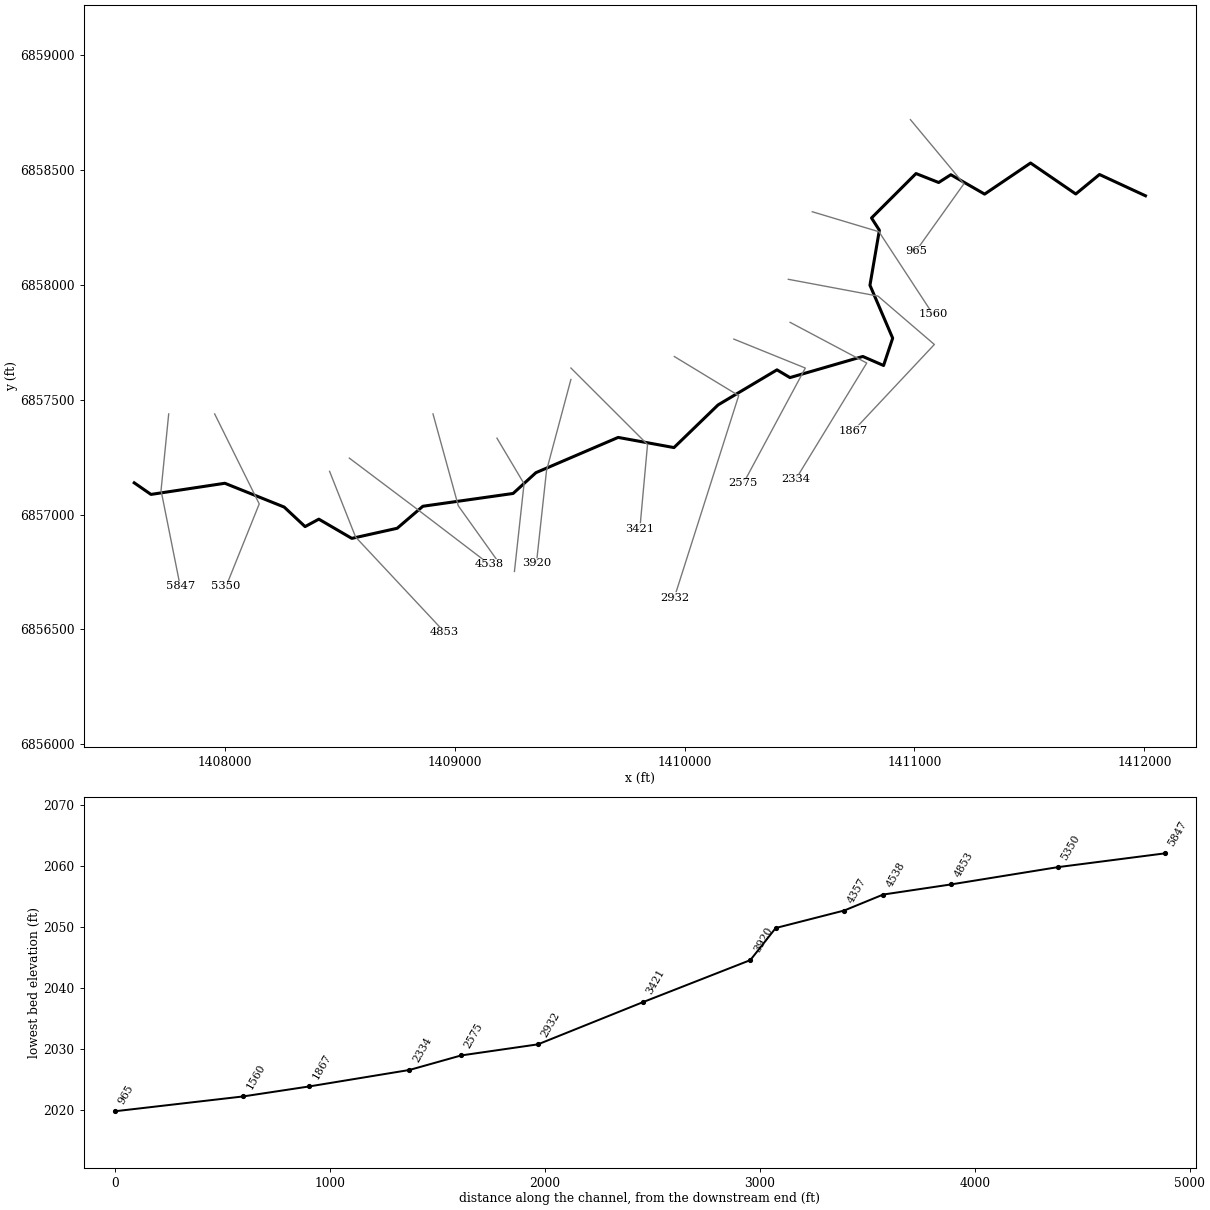
--- Bitter Creek Trib15.prj (project) ---

Proj Title=Bitter Creek Trib15 Base Level Engineering
Current Plan=p01
Default Exp/Contr=0.3,0.1
English Units
Geom File=g01
Flow File=f01
Plan File=p01
Y Axis Title=Elevation
X Axis Title(PF)=Main Channel Distance
X Axis Title(XS)=Station
BEGIN DESCRIPTION:
Bitter Creek Trib15
END DESCRIPTION:
DSS Export Rating Curves= 0
DSS Export Rating Curve Sorted= 0
DSS Export Volume Flow Curves= 0
DXF OffsetX= 0
DXF OffsetY= 0
DXF ScaleX= 1
DXF ScaleY= 10

--- Bitter Creek Trib15.p01 (plan) ---

Plan Title=Multiple Run
Short Identifier=Multiple
Geom File=g01
Flow File=f01
Subcritical Flow
K Sum by GR= 0
Std Step Tol= 0.01
Critical Tol= 0.01
Num of Std Step Trials= 20
Max Error Tol= 0.3
Flow Tol Ratio= 0.001
Split Flow NTrial= 30
Split Flow Tol= 0.02
Split Flow Ratio= 0.02
Log Output Level= 0
Friction Slope Method= 1
Unsteady Friction Slope Method= 2
Unsteady Bridges Friction Slope Method= 1
Parabolic Critical Depth
Global Vel Dist=  1 , 1 , 1
Global Log Level= 0
CheckData=True
Encroach Param= -1, 0, 0, 0
BEGIN DESCRIPTION:
Multiple Run
END DESCRIPTION:

--- Bitter Creek Trib15.f01 (steady flow) ---

Flow Title=Multiple
Number of Profiles=7
Profile Names=10-year,25-year,50-year,1pct_min,100-year,1pct_plu,500-year
River Rch & RM= Bitter Creek Tri,Reach-1,5847
     393     568     718     451     900    1796    1434
Boundary for River Rch & Prof#=Bitter Creek Tri,Reach-1,1
Up Type=0
Dn Type=3
Dn Slope=0.005
Boundary for River Rch & Prof#=Bitter Creek Tri,Reach-1,2
Up Type=0
Dn Type=3
Dn Slope=0.005
Boundary for River Rch & Prof#=Bitter Creek Tri,Reach-1,3
Up Type=0
Dn Type=3
Dn Slope=0.005
Boundary for River Rch & Prof#=Bitter Creek Tri,Reach-1,4
Up Type=0
Dn Type=3
Dn Slope=0.005
Boundary for River Rch & Prof#=Bitter Creek Tri,Reach-1,5
Up Type=0
Dn Type=3
Dn Slope=0.005
Boundary for River Rch & Prof#=Bitter Creek Tri,Reach-1,6
Up Type=0
Dn Type=3
Dn Slope=0.005
Boundary for River Rch & Prof#=Bitter Creek Tri,Reach-1,7
Up Type=0
Dn Type=3
Dn Slope=0.005

--- Bitter Creek Trib15.g01 (geometry) ---

Geom Title=Existing Conditions

River Reach=Bitter Creek Tri,Reach-1
Reach XY= 30
      1407605.00      6857138.00      1407677.89      6857087.49
      1407999.30      6857136.08      1408257.43      6857032.45
      1408348.34      6856947.32      1408408.23      6856979.75
      1408551.68      6856896.04      1408749.14      6856940.08
      1408860.86      6857035.93      1409253.50      6857091.62
      1409352.71      6857182.15      1409710.56      6857335.74
      1409953.50      6857291.46      1410145.32      6857477.24
      1410401.67      6857629.99      1410458.21      6857596.29
      1410775.21      6857688.21      1410865.44      6857648.96
      1410905.10      6857767.88      1410806.22      6857998.50
      1410847.19      6858238.10      1410812.99      6858291.34
      1411006.65      6858484.84      1411105.08      6858445.83
      1411158.23      6858479.76      1411305.08      6858395.30
      1411505.08      6858530.70      1411701.77      6858395.85
      1411804.91      6858480.69      1412005.00      6858388.00

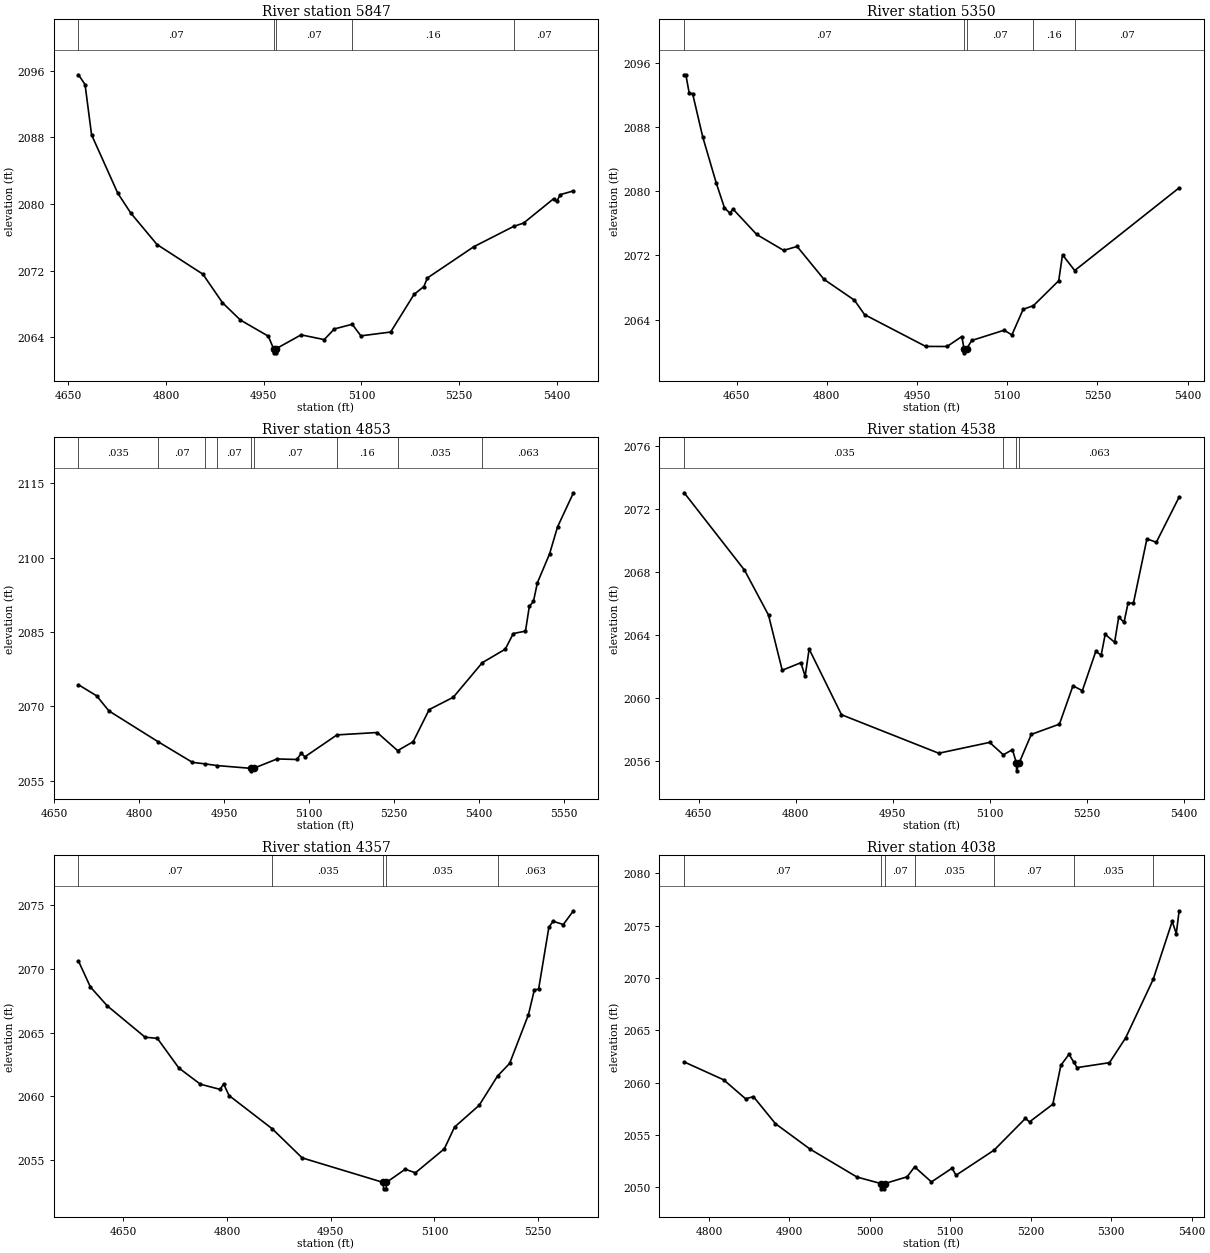
Type RM Length L Ch R = 1,5847,497,497,497
BEGIN DESCRIPTION:
Bitter Creek Trib15 6.0
END DESCRIPTION:
XS GIS Cut Line= 3
      1407755.00      6857438.01      1407721.67      6857105.17
      1407805.00      6856688.01
#Sta/Elev= 30
  4665.5 2095.51  4675.6 2094.34  4685.6 2088.30  4725.8 2081.29  4745.9 2078.89
  4786.1 2075.12  4856.5 2071.56  4886.6 2068.13  4914.1 2066.05  4957.0 2064.11
  4965.0 2062.61  4965.2 2062.11  4968.8 2062.11  4969.1 2062.61  5007.3 2064.27
  5042.8 2063.70  5058.3 2064.98  5085.7 2065.54  5099.1 2064.15  5144.8 2064.61
  5180.7 2069.13  5195.8 2070.07  5201.1 2071.10  5272.5 2074.86  5333.4 2077.29
  5348.9 2077.70  5394.8 2080.61  5399.9 2080.29  5405.0 2081.11  5425.4 2081.56
#Mann=5,-1,0
  4665.5    0.07       0  4965.0    0.07       0  4969.1    0.07       0
  5085.7    0.16       0  5333.4    0.07       0
Bank Sta=4965,4969.1
Exp/Cntr=0.3,0.1

Type RM Length L Ch R = 1,5350,497,497,497
BEGIN DESCRIPTION:
Bitter Creek Trib15 5.0
END DESCRIPTION:
XS GIS Cut Line= 3
      1407955.01      6857437.98      1408148.95      6857046.15
      1408005.00      6856687.99
#Sta/Elev= 30
  4562.8 2094.48  4565.6 2094.48  4571.2 2092.17  4576.8 2092.14  4593.6 2086.75
  4616.1 2081.01  4629.7 2077.93  4638.5 2077.26  4644.1 2077.75  4683.4 2074.59
  4728.2 2072.61  4750.6 2073.10  4795.5 2068.99  4845.9 2066.41  4862.8 2064.61
  4964.5 2060.65  5000.0 2060.64  5024.5 2061.88  5028.3 2060.35  5028.5 2059.85
  5032.4 2060.35  5041.1 2061.39  5095.0 2062.67  5107.8 2062.08  5126.6 2065.27
  5143.7 2065.73  5185.7 2068.83  5192.0 2072.06  5212.3 2070.10  5386.0 2080.40
#Mann=5,-1,0
  4562.8    0.07       0  5028.3    0.07       0  5032.4    0.07       0
  5143.7    0.16       0  5212.3    0.07       0
Bank Sta=5028.3,5032.4
Exp/Cntr=0.3,0.1

Type RM Length L Ch R = 1,4853,315,315,315
BEGIN DESCRIPTION:
Bitter Creek Trib15 4.0
END DESCRIPTION:
XS GIS Cut Line= 3
      1408455.02      6857187.96      1408568.20      6856901.94
      1408954.98      6856488.02
#Sta/Elev= 30
  4692.4 2074.37  4724.6 2072.13  4746.1 2069.10  4833.3 2062.86  4893.7 2058.72
  4916.3 2058.41  4937.5 2058.07  4997.3 2057.51  4997.6 2057.01  5001.5 2057.51
  5043.1 2059.41  5078.3 2059.30  5085.6 2060.55  5092.4 2059.85  5148.9 2064.26
  5219.9 2064.74  5256.0 2061.09  5283.4 2062.88  5311.8 2069.37  5354.3 2071.85
  5405.6 2078.83  5446.1 2081.55  5460.3 2084.70  5481.8 2085.19  5488.6 2090.18
  5495.9 2091.19  5502.8 2094.93  5524.3 2100.75  5538.4 2106.20  5566.5 2113.09
#Mann=9,-1,0
  4692.4   0.035       0  4833.3    0.07       0  4916.3   0.035       0
  4937.5    0.07       0  4997.3    0.07       0  5001.5    0.07       0
  5148.9    0.16       0  5256.0   0.035       0  5405.6   0.063       0
Bank Sta=4997.3,5001.5
Exp/Cntr=0.3,0.1

Type RM Length L Ch R = 1,4538,181,181,181
BEGIN DESCRIPTION:
Bitter Creek Trib15 4283
END DESCRIPTION:
XS GIS Cut Line= 3
      1408540.93      6857245.61      1408838.25      6857021.53
      1409150.25      6856783.23
#Sta/Elev= 30
  4627.7 2073.04  4720.9 2068.12  4758.0 2065.26  4779.2 2061.75  4808.1 2062.23
  4814.6 2061.36  4820.8 2063.10  4870.8 2058.92  5021.1 2056.47  5099.7 2057.16
  5120.9 2056.37  5135.0 2056.70  5141.1 2055.85  5141.4 2055.35  5145.3 2055.85
  5164.1 2057.67  5207.6 2058.32  5228.5 2060.76  5243.0 2060.45  5263.8 2062.95
  5272.1 2062.71  5278.3 2064.03  5292.9 2063.53  5299.2 2065.13  5307.4 2064.80
  5313.7 2066.03  5321.9 2066.01  5342.8 2070.11  5357.3 2069.89  5392.6 2072.77
#Mann=4,-1,0
  4627.7   0.035       0  5120.9   0.063       0  5141.1   0.035       0
  5145.3   0.063       0
Bank Sta=5141.1,5145.3
Exp/Cntr=0.3,0.1

Type RM Length L Ch R = 1,4357,319,319,319
BEGIN DESCRIPTION:
Bitter Creek Trib15 3.0
END DESCRIPTION:
XS GIS Cut Line= 3
      1408904.99      6857438.03      1409015.05      6857037.89
      1409189.84      6856792.85
#Sta/Elev= 30
  4585.0 2070.62  4602.2 2068.59  4626.5 2067.11  4681.4 2064.64  4699.1 2064.55
  4730.2 2062.22  4761.3 2060.95  4789.9 2060.54  4795.0 2060.97  4802.8 2060.06
  4865.2 2057.45  4908.6 2055.16  5026.0 2053.23  5026.3 2052.73  5030.1 2052.73
  5030.3 2053.23  5057.7 2054.27  5072.4 2053.99  5114.2 2055.87  5129.0 2057.58
  5164.6 2059.29  5191.2 2061.59  5208.7 2062.58  5235.9 2066.41  5244.5 2068.37
  5250.6 2068.41  5265.4 2073.26  5271.5 2073.75  5286.3 2073.49  5301.0 2074.57
#Mann=5,-1,0
  4585.0    0.07       0  4865.2   0.035       0  5026.0   0.035       0
  5030.3   0.035       0  5191.2   0.063       0
Bank Sta=5026,5030.3
Exp/Cntr=0.3,0.1

Type RM Length L Ch R = 1,4038,118,118,118
BEGIN DESCRIPTION:
Bitter Creek Trib15 4282
END DESCRIPTION:
XS GIS Cut Line= 3
      1409183.26      6857332.44      1409301.17      6857134.03
      1409259.33      6856751.91
#Sta/Elev= 30
  4769.2 2061.98  4818.3 2060.27  4845.5 2058.46  4855.3 2058.66  4882.6 2056.08
  4925.6 2053.65  4983.9 2050.98  5013.9 2050.35  5014.2 2049.85  5018.0 2049.85
  5018.3 2050.35  5046.3 2051.00  5055.6 2051.95  5076.5 2050.51  5102.1 2051.82
  5107.1 2051.15  5154.4 2053.55  5193.3 2056.58  5198.4 2056.25  5227.4 2057.94
  5237.4 2061.66  5247.5 2062.71  5253.2 2061.99  5257.6 2061.44  5297.8 2061.91
  5317.9 2064.28  5352.1 2069.87  5375.8 2075.42  5380.8 2074.24  5384.4 2076.43
#Mann=7,-1,0
  4769.2    0.07       0  5013.9    0.07       0  5018.3    0.07       0
  5055.6   0.035       0  5154.4    0.07       0  5253.2   0.035       0
  5352.1   0.063       0
Bank Sta=5013.9,5018.3
Exp/Cntr=0.3,0.1

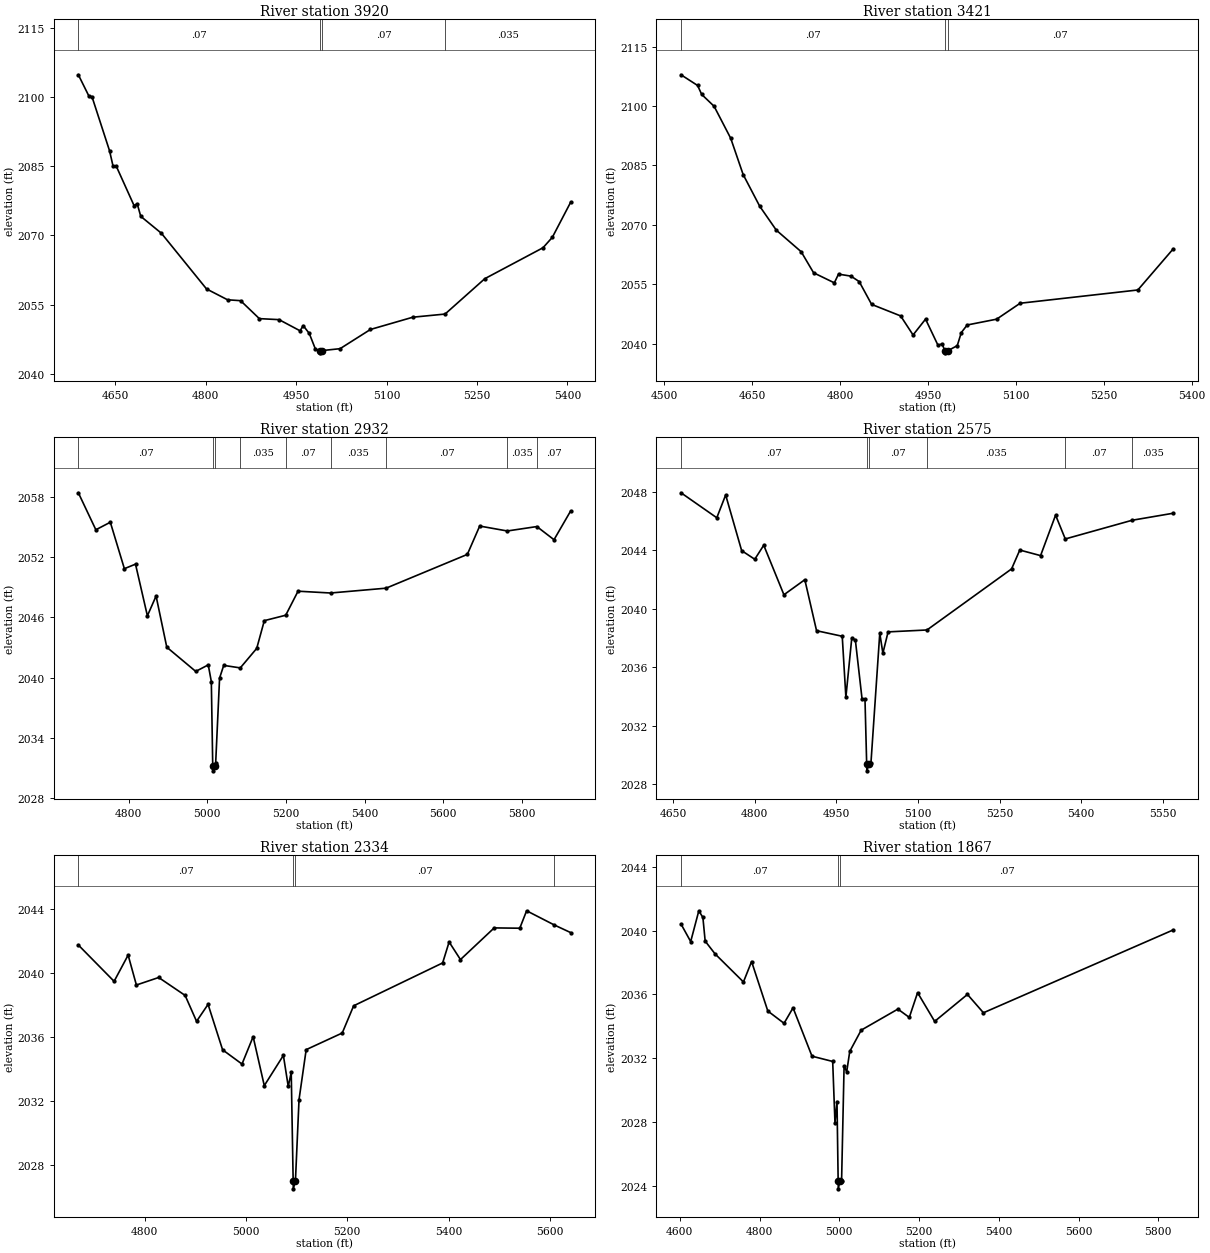
Type RM Length L Ch R = 1,3920,499,499,499
BEGIN DESCRIPTION:
Bitter Creek Trib15 2.0
END DESCRIPTION:
XS GIS Cut Line= 3
      1409505.00      6857588.00      1409398.87      6857190.74
      1409355.00      6856788.02
#Sta/Elev= 30
  4588.8 2104.81  4606.3 2100.20  4611.4 2100.07  4640.6 2088.33  4646.3 2085.06
  4651.5 2085.07  4681.2 2076.48  4686.4 2076.88  4692.3 2074.15  4726.5 2070.49
  4801.4 2058.42  4836.3 2056.07  4857.9 2055.88  4889.0 2051.99  4921.7 2051.77
  4956.6 2049.35  4961.7 2050.49  4971.8 2048.78  4982.1 2045.35  4989.3 2045.08
  4989.6 2044.58  4993.7 2045.08  5022.9 2045.48  5073.2 2049.64  5143.6 2052.30
  5197.0 2052.98  5262.9 2060.64  5359.4 2067.34  5374.9 2069.60  5405.1 2077.15
#Mann=4,-1,0
  4588.8    0.07       0  4989.3    0.07       0  4993.7    0.07       0
  5197.0   0.035       0
Bank Sta=4989.3,4993.7
Exp/Cntr=0.3,0.1

Type RM Length L Ch R = 1,3421,489,489,489
BEGIN DESCRIPTION:
Bitter Creek Trib15 1.0
END DESCRIPTION:
XS GIS Cut Line= 3
      1409505.02      6857637.98      1409838.43      6857304.87
      1409805.00      6856937.99
#Sta/Elev= 30
  4528.7 2107.88  4557.0 2105.18  4564.0 2102.92  4585.2 2099.92  4613.5 2091.85
  4634.7 2082.70  4663.0 2074.69  4691.3 2068.65  4733.7 2063.21  4754.9 2057.89
  4790.3 2055.35  4797.4 2057.55  4818.6 2057.05  4832.7 2055.67  4853.9 2049.91
  4903.4 2047.00  4924.6 2042.19  4945.9 2046.19  4967.1 2039.60  4974.1 2039.93
  4979.0 2038.18  4979.3 2037.68  4983.4 2038.18  5000.0 2039.49  5006.9 2042.79
  5016.9 2044.71  5067.2 2046.18  5107.3 2050.20  5308.1 2053.55  5368.4 2063.92
#Mann=3,-1,0
  4528.7    0.07       0  4979.0    0.07       0  4983.4    0.07       0
Bank Sta=4979,4983.4
Exp/Cntr=0.3,0.1

Type RM Length L Ch R = 1,2932,357,357,357
BEGIN DESCRIPTION:
Bitter Creek Trib15 0.1
END DESCRIPTION:
XS GIS Cut Line= 3
      1409955.02      6857687.99      1410235.07      6857517.82
      1409955.01      6856638.03
#Sta/Elev= 30
  4672.3 2058.40  4716.8 2054.72  4753.6 2055.47  4789.3 2050.85  4817.6 2051.30
  4847.8 2046.16  4869.9 2048.13  4897.1 2043.04  4970.7 2040.63  5002.5 2041.28
  5010.3 2039.62  5013.9 2031.24  5014.2 2030.74  5018.4 2031.24  5021.4 2031.55
  5031.3 2039.97  5041.8 2041.23  5083.9 2040.98  5125.7 2042.92  5145.0 2045.68
  5199.4 2046.22  5230.7 2048.61  5313.3 2048.43  5454.4 2048.91  5661.0 2052.27
  5692.4 2055.09  5762.5 2054.60  5837.7 2055.04  5881.3 2053.73  5923.3 2056.57
#Mann=9,-1,0
  4672.3    0.07       0  5013.9    0.07       0  5018.4    0.07       0
  5083.9   0.035       0  5199.4    0.07       0  5313.3   0.035       0
  5454.4    0.07       0  5762.5   0.035       0  5837.7    0.07       0
Bank Sta=5013.9,5018.4
Exp/Cntr=0.3,0.1

Type RM Length L Ch R = 1,2575,241,241,241
BEGIN DESCRIPTION:
Bitter Creek Trib15 4287
END DESCRIPTION:
XS GIS Cut Line= 3
      1410214.06      6857763.87      1410524.98      6857637.82
      1410255.72      6857136.22
#Sta/Elev= 30
  4664.5 2047.95  4730.3 2046.24  4746.6 2047.80  4776.0 2043.99  4800.1 2043.40
  4816.6 2044.36  4853.7 2040.97  4892.1 2042.00  4913.7 2038.51  4960.9 2038.13
  4967.6 2033.96  4978.4 2038.00  4985.0 2037.88  4997.3 2033.85  5002.7 2033.85
  5005.8 2029.42  5006.1 2028.92  5010.3 2029.42  5013.7 2029.47  5029.9 2038.34
  5035.6 2036.97  5045.2 2038.43  5116.7 2038.56  5272.2 2042.74  5287.3 2044.03
  5325.5 2043.65  5353.1 2046.42  5370.9 2044.79  5493.9 2046.07  5569.3 2046.55
#Mann=6,-1,0
  4664.5    0.07       0  5005.8    0.07       0  5010.3    0.07       0
  5116.7   0.035       0  5370.9    0.07       0  5493.9   0.035       0
Bank Sta=5005.8,5010.3
Exp/Cntr=0.3,0.1

Type RM Length L Ch R = 1,2334,467,467,467
BEGIN DESCRIPTION:
Bitter Creek Trib15 4288
END DESCRIPTION:
XS GIS Cut Line= 3
      1410458.84      6857836.80      1410792.20      6857659.70
      1410482.66      6857152.47
#Sta/Elev= 30
  4669.0 2041.77  4739.6 2039.50  4767.3 2041.14  4783.6 2039.27  4827.6 2039.74
  4879.8 2038.62  4902.4 2037.00  4925.1 2038.06  4953.8 2035.22  4992.1 2034.33
  5014.1 2036.04  5036.1 2032.98  5073.8 2034.87  5083.4 2032.93  5089.3 2033.81
  5093.1 2027.03  5093.4 2026.53  5097.6 2027.03  5104.7 2032.11  5118.8 2035.23
  5190.0 2036.27  5212.5 2037.97  5388.2 2040.65  5401.0 2041.96  5423.4 2040.86
  5490.0 2042.84  5540.5 2042.82  5554.0 2043.91  5608.8 2043.02  5640.7 2042.55
#Mann=4,-1,0
  4669.0    0.07       0  5093.1    0.07       0  5097.6    0.07       0
  5608.8   0.035       0
Bank Sta=5093.1,5097.6
Exp/Cntr=0.3,0.1

Type RM Length L Ch R = 1,1867,307,307,307
BEGIN DESCRIPTION:
Bitter Creek Trib15 4289
END DESCRIPTION:
XS GIS Cut Line= 4
      1410451.07      6858024.28      1410841.17      6857951.13
      1411086.47      6857740.43      1410734.91      6857365.42
#Sta/Elev= 30
  4603.1 2040.41  4627.4 2039.31  4647.8 2041.24  4658.0 2040.82  4663.7 2039.34
  4688.5 2038.54  4759.7 2036.78  4780.1 2038.06  4820.8 2034.96  4861.5 2034.19
  4884.1 2035.16  4931.6 2032.13  4983.5 2031.80  4989.2 2027.97  4994.3 2029.29
  4997.2 2024.32  4997.5 2023.82  5001.7 2024.32  5005.8 2024.32  5012.1 2031.53
  5018.6 2031.15  5026.3 2032.43  5054.9 2033.76  5147.0 2035.08  5175.6 2034.56
  5196.4 2036.11  5239.2 2034.31  5321.4 2036.00  5361.5 2034.85  5837.4 2040.04
#Mann=3,-1,0
  4603.1    0.07       0  4997.2    0.07       0  5001.7    0.07       0
Bank Sta=4997.2,5001.7
Exp/Cntr=0.3,0.1

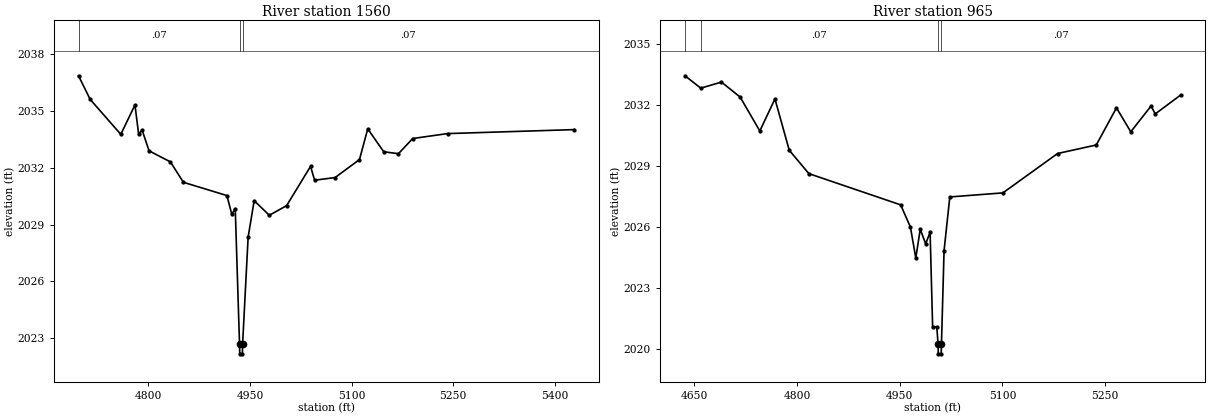
Type RM Length L Ch R = 1,1560,595,595,595
BEGIN DESCRIPTION:
Bitter Creek Trib15 4290
END DESCRIPTION:
XS GIS Cut Line= 3
      1410555.25      6858318.54      1410845.36      6858231.47
      1411079.84      6857872.81
#Sta/Elev= 30
  4697.1 2036.85  4714.4 2035.60  4759.5 2033.76  4780.4 2035.31  4785.8 2033.78
  4791.0 2033.98  4801.2 2032.89  4832.6 2032.31  4851.9 2031.23  4916.1 2030.53
  4923.2 2029.55  4928.4 2029.84  4934.7 2022.68  4935.0 2022.18  4938.9 2022.18
  4939.2 2022.68  4947.4 2028.34  4956.3 2030.26  4978.7 2029.49  5004.2 2030.00
  5039.5 2032.07  5045.5 2031.34  5075.7 2031.48  5111.7 2032.43  5123.9 2034.05
  5147.5 2032.84  5169.2 2032.74  5190.3 2033.54  5241.6 2033.80  5428.5 2034.01
#Mann=3,-1,0
  4697.1    0.07       0  4934.7    0.07       0  4939.2    0.07       0
Bank Sta=4934.7,4939.2
Exp/Cntr=0.3,0.1

Type RM Length L Ch R = 1,965,0,0,0
BEGIN DESCRIPTION:
Bitter Creek Trib15 4291
END DESCRIPTION:
XS GIS Cut Line= 3
      1410982.29      6858719.62      1411214.80      6858439.94
      1411005.72      6858146.64
#Sta/Elev= 30
  4636.3 2033.45  4659.4 2032.84  4689.6 2033.14  4716.9 2032.40  4745.6 2030.73
  4767.7 2032.31  4788.6 2029.78  4817.2 2028.63  4951.3 2027.09  4965.6 2025.99
  4973.4 2024.47  4979.9 2025.89  4987.8 2025.17  4994.3 2025.74  4998.0 2021.07
  5004.1 2021.07  5005.9 2020.25  5006.3 2019.75  5010.5 2019.75  5010.9 2020.25
  5014.7 2024.84  5023.1 2027.48  5100.6 2027.68  5180.5 2029.62  5237.0 2030.04
  5266.5 2031.87  5287.4 2030.69  5317.0 2031.96  5323.1 2031.57  5360.2 2032.50
#Mann=4,-1,0
  4636.3   0.035       0  4659.4    0.07       0  5005.9    0.07       0
  5010.9    0.07       0
Bank Sta=5005.9,5010.9
Exp/Cntr=0.3,0.1

Chan Stop Cuts=-1