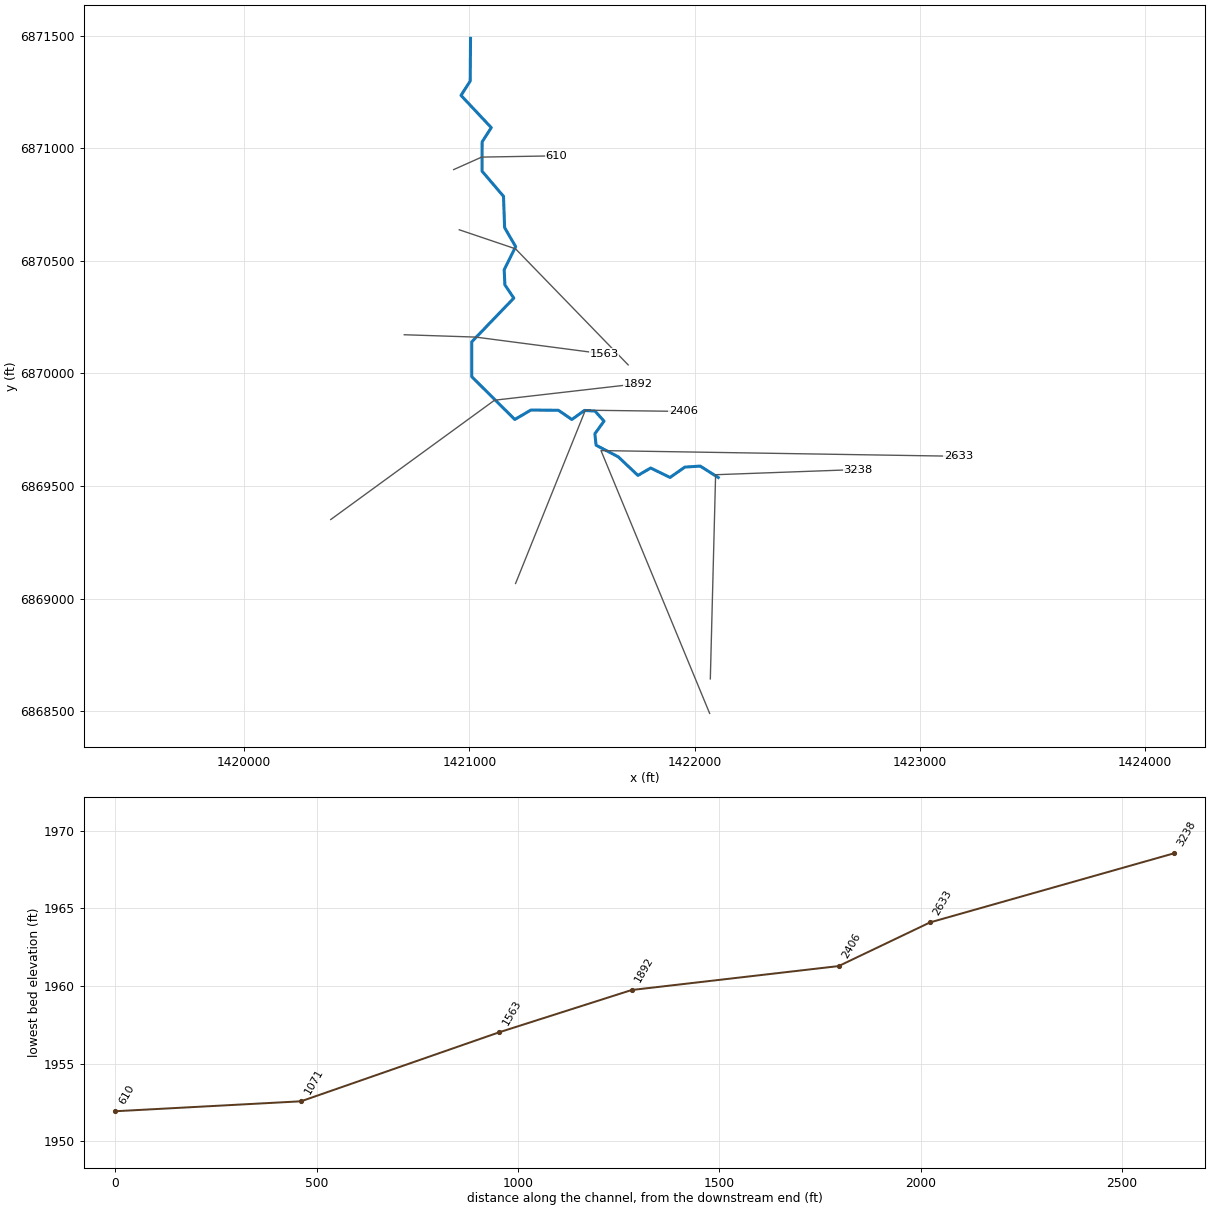
--- Bitter Creek Trib16.prj (project) ---

Proj Title=Bitter Creek Trib16 Base Level Engineering
Current Plan=p01
Default Exp/Contr=0.3,0.1
English Units
Geom File=g01
Flow File=f01
Plan File=p01
Y Axis Title=Elevation
X Axis Title(PF)=Main Channel Distance
X Axis Title(XS)=Station
BEGIN DESCRIPTION:
Bitter Creek Trib16
END DESCRIPTION:
DSS Export Rating Curves= 0
DSS Export Rating Curve Sorted= 0
DSS Export Volume Flow Curves= 0
DXF OffsetX= 0
DXF OffsetY= 0
DXF ScaleX= 1
DXF ScaleY= 10

--- Bitter Creek Trib16.p01 (plan) ---

Plan Title=Multiple Run
Short Identifier=Multiple
Geom File=g01
Flow File=f01
Subcritical Flow
K Sum by GR= 0
Std Step Tol= 0.01
Critical Tol= 0.01
Num of Std Step Trials= 20
Max Error Tol= 0.3
Flow Tol Ratio= 0.001
Split Flow NTrial= 30
Split Flow Tol= 0.02
Split Flow Ratio= 0.02
Log Output Level= 0
Friction Slope Method= 1
Unsteady Friction Slope Method= 2
Unsteady Bridges Friction Slope Method= 1
Parabolic Critical Depth
Global Vel Dist=  1 , 1 , 1
Global Log Level= 0
CheckData=True
Encroach Param= -1, 0, 0, 0
BEGIN DESCRIPTION:
Multiple Run
END DESCRIPTION:

--- Bitter Creek Trib16.f01 (steady flow) ---

Flow Title=Multiple
Number of Profiles=7
Profile Names=10-year,25-year,50-year,1pct_min,100-year,1pct_plu,500-year
River Rch & RM= Bitter Creek Tri,Reach-1,3238
     230     321     397     244     487     972     742
Boundary for River Rch & Prof#=Bitter Creek Tri,Reach-1,1
Up Type=0
Dn Type=3
Dn Slope=0.005
Boundary for River Rch & Prof#=Bitter Creek Tri,Reach-1,2
Up Type=0
Dn Type=3
Dn Slope=0.005
Boundary for River Rch & Prof#=Bitter Creek Tri,Reach-1,3
Up Type=0
Dn Type=3
Dn Slope=0.005
Boundary for River Rch & Prof#=Bitter Creek Tri,Reach-1,4
Up Type=0
Dn Type=3
Dn Slope=0.005
Boundary for River Rch & Prof#=Bitter Creek Tri,Reach-1,5
Up Type=0
Dn Type=3
Dn Slope=0.005
Boundary for River Rch & Prof#=Bitter Creek Tri,Reach-1,6
Up Type=0
Dn Type=3
Dn Slope=0.005
Boundary for River Rch & Prof#=Bitter Creek Tri,Reach-1,7
Up Type=0
Dn Type=3
Dn Slope=0.005

--- Bitter Creek Trib16.g01 (geometry) ---

Geom Title=Existing Conditions

River Reach=Bitter Creek Tri,Reach-1
Reach XY= 30
      1422105.00      6869538.00      1422025.03      6869588.64
      1421956.57      6869584.27      1421890.87      6869538.30
      1421804.91      6869580.16      1421748.34      6869547.31
      1421661.03      6869629.80      1421562.39      6869681.67
      1421557.10      6869732.33      1421597.74      6869788.36
      1421557.85      6869832.89      1421510.72      6869835.90
      1421455.02      6869795.59      1421395.40      6869836.46
      1421273.23      6869837.68      1421201.58      6869795.79
      1421010.45      6869985.55      1421010.45      6870140.45
      1421197.20      6870334.58      1421157.50      6870393.48
      1421154.52      6870460.75      1421205.40      6870563.00
      1421156.41      6870647.66      1421151.44      6870786.53
      1421056.04      6870898.44      1421056.54      6871028.41
      1421097.20      6871091.42      1420962.79      6871234.58
      1421003.62      6871298.43      1421005.00      6871488.00

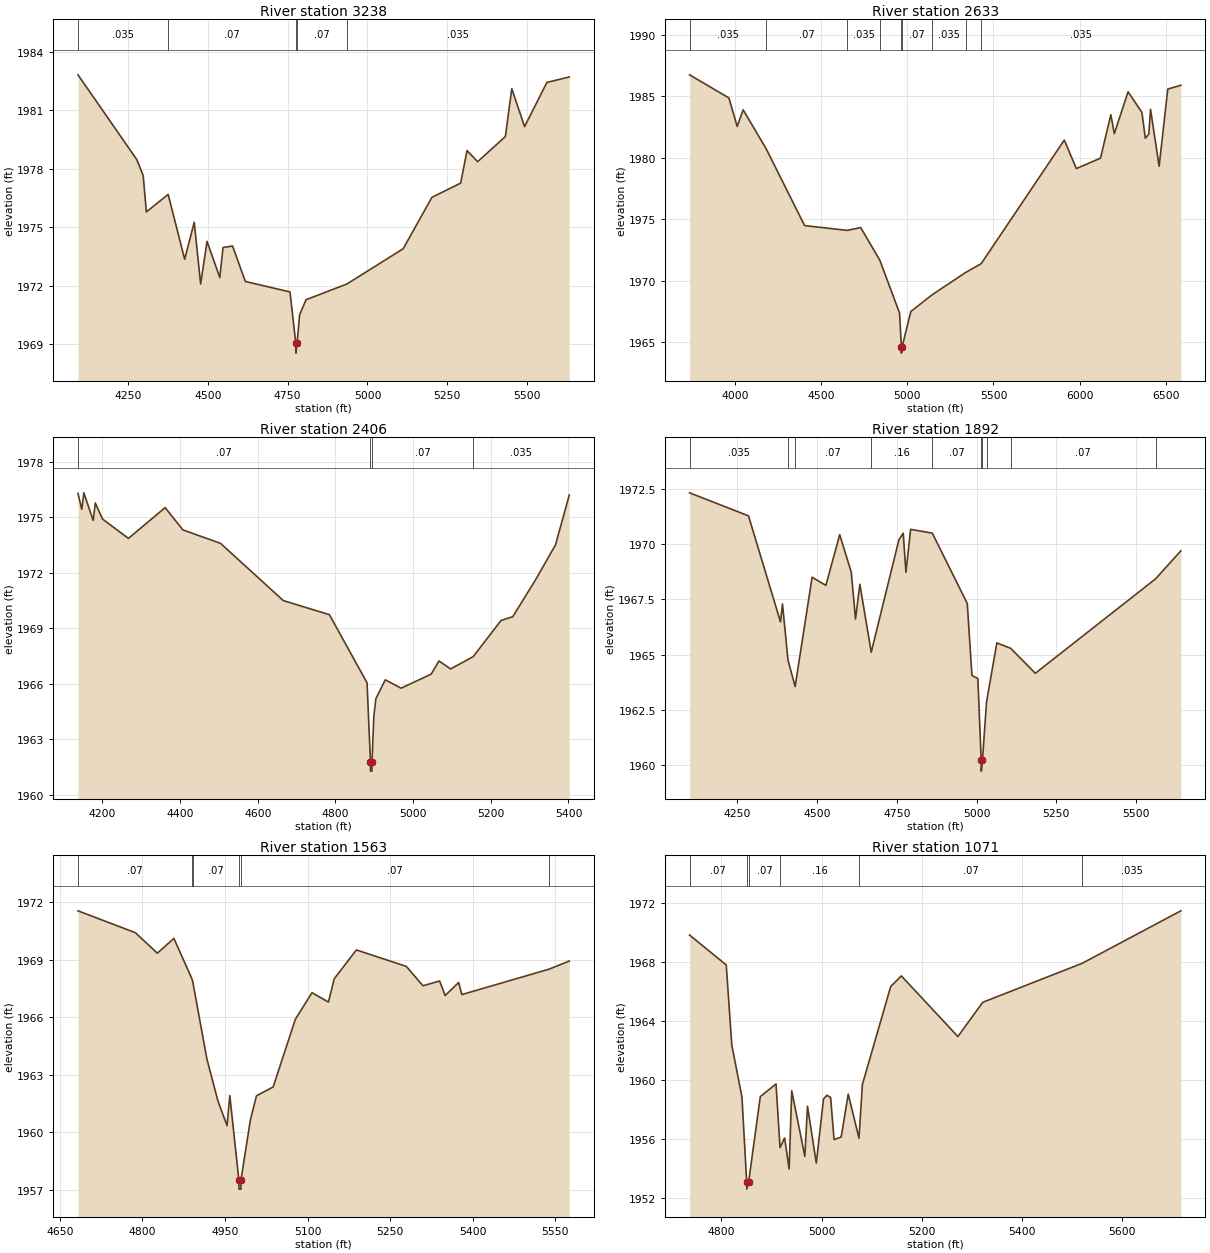
Type RM Length L Ch R = 1,3238,605,605,605
BEGIN DESCRIPTION:
Bitter Creek Trib16 6.0
END DESCRIPTION:
XS GIS Cut Line= 3
      1422069.73      6868643.88      1422093.18      6869550.47
      1422724.95      6869573.55
#Sta/Elev= 30
  4093.1 1982.82  4277.3 1978.47  4297.3 1977.65  4307.3 1975.78  4375.6 1976.68
  4427.3 1973.35  4457.3 1975.25  4477.4 1972.08  4497.4 1974.27  4537.4 1972.41
  4547.4 1973.95  4577.4 1974.03  4617.4 1972.21  4757.4 1971.67  4775.5 1969.03
  4775.7 1968.53  4779.5 1969.03  4787.5 1970.50  4807.5 1971.27  4935.7 1972.08
  5111.9 1973.89  5202.0 1976.53  5292.0 1977.26  5312.0 1978.93  5345.1 1978.36
  5432.1 1979.65  5452.1 1982.11  5492.2 1980.16  5562.2 1982.43  5632.2 1982.71
#Mann=5,-1,0
  4093.1   0.035       0  4375.6    0.07       0  4775.5   0.035       0
  4779.5    0.07       0  4935.7   0.035       0
Bank Sta=4775.5,4779.5
Exp/Cntr=0.3,0.1

Type RM Length L Ch R = 1,2633,227,227,227
BEGIN DESCRIPTION:
Bitter Creek Trib16 5.0
END DESCRIPTION:
XS GIS Cut Line= 3
      1422066.68      6868490.80      1421584.32      6869657.63
      1423170.92      6869632.29
#Sta/Elev= 30
  3737.4 1986.74  3965.6 1984.86  4013.5 1982.54  4048.2 1983.89  4182.6 1980.70
  4404.6 1974.47  4652.3 1974.08  4729.9 1974.31  4840.9 1971.65  4955.3 1967.35
  4965.9 1964.59  4966.2 1964.09  4969.9 1964.59  5020.7 1967.48  5143.5 1968.83
  5338.1 1970.65  5428.8 1971.37  5910.8 1981.43  5980.8 1979.11  6120.8 1979.96
  6180.8 1983.49  6200.8 1981.95  6280.8 1985.36  6360.9 1983.68  6380.9 1981.58
  6400.9 1981.91  6410.9 1983.93  6460.9 1979.30  6510.9 1985.58  6586.8 1985.89
#Mann=9,-1,0
  3737.4   0.035       0  4182.6    0.07       0  4652.3   0.035       0
  4840.9    0.07       0  4965.9    0.07       0  4969.9    0.07       0
  5143.5   0.035       0  5338.1    0.07       0  5428.8   0.035       0
Bank Sta=4965.9,4969.9
Exp/Cntr=0.3,0.1

Type RM Length L Ch R = 1,2406,514,514,514
BEGIN DESCRIPTION:
Bitter Creek Trib16 4.0
END DESCRIPTION:
XS GIS Cut Line= 3
      1421205.00      6869067.49      1421514.89      6869836.95
      1421950.44      6869831.52
#Sta/Elev= 30
  4136.9 1976.28  4146.6 1975.42  4152.0 1976.31  4176.1 1974.82  4181.5 1975.76
  4200.3 1974.89  4266.8 1973.85  4361.4 1975.51  4407.0 1974.31  4504.0 1973.58
  4665.7 1970.49  4784.3 1969.73  4881.3 1966.05  4890.1 1961.78  4890.3 1961.28
  4893.8 1961.28  4894.1 1961.78  4898.6 1964.22  4904.0 1965.19  4928.2 1966.21
  4969.0 1965.76  5046.5 1966.52  5066.5 1967.23  5096.5 1966.80  5154.5 1967.46
  5226.5 1969.42  5256.5 1969.62  5316.6 1971.66  5366.6 1973.50  5402.0 1976.19
#Mann=4,-1,0
  4136.9    0.07       0  4890.1    0.07       0  4894.1    0.07       0
  5154.5   0.035       0
Bank Sta=4890.1,4894.1
Exp/Cntr=0.3,0.1

Type RM Length L Ch R = 1,1892,329,329,329
BEGIN DESCRIPTION:
Bitter Creek Trib16 3.0
END DESCRIPTION:
XS GIS Cut Line= 3
      1420384.37      6869351.49      1421111.66      6869881.29
      1421748.27      6869954.42
#Sta/Elev= 30
  4100.2 1972.31  4285.0 1971.27  4385.4 1966.48  4391.6 1967.29  4408.8 1964.76
  4431.2 1963.56  4484.5 1968.50  4527.6 1968.13  4571.1 1970.42  4607.2 1968.73
  4620.6 1966.61  4634.2 1968.18  4669.9 1965.11  4756.7 1970.19  4770.2 1970.49
  4778.7 1968.72  4793.4 1970.66  4861.4 1970.49  4971.1 1967.31  4985.7 1964.06
  5004.2 1963.92  5014.7 1960.24  5015.0 1959.74  5018.7 1960.24  5031.4 1962.86
  5063.8 1965.53  5107.0 1965.29  5184.5 1964.16  5562.0 1968.43  5640.8 1969.69
#Mann=10,-1,0
  4100.2   0.035       0  4408.8    0.16       0  4431.2    0.07       0
  4669.9    0.16       0  4861.4    0.07       0  5014.7    0.07       0
  5018.7    0.07       0  5031.4    0.16       0  5107.0    0.07       0
  5562.0   0.035       0
Bank Sta=5014.7,5018.7
Exp/Cntr=0.3,0.1

Type RM Length L Ch R = 1,1563,492,492,492
BEGIN DESCRIPTION:
Bitter Creek Trib16 2.0
END DESCRIPTION:
XS GIS Cut Line= 3
      1420710.83      6870171.94      1421027.86      6870161.53
      1421598.59      6870086.81
#Sta/Elev= 30
  4682.8 1971.54  4787.0 1970.40  4827.1 1969.33  4857.1 1970.10  4889.5 1968.02
  4891.4 1967.84  4917.1 1963.81  4937.1 1961.62  4953.7 1960.33  4958.7 1961.90
  4975.1 1957.52  4975.4 1957.02  4978.9 1957.02  4979.1 1957.52  4996.1 1960.63
  5007.2 1961.89  5037.5 1962.35  5077.8 1965.88  5108.1 1967.27  5138.0 1966.78
  5148.4 1967.99  5188.7 1969.50  5279.5 1968.64  5309.8 1967.63  5340.0 1967.88
  5350.1 1967.12  5374.6 1967.80  5380.4 1967.17  5539.3 1968.50  5575.6 1968.92
#Mann=6,-1,0
  4682.8    0.07       0  4889.5    0.16       0  4891.4    0.07       0
  4975.1    0.07       0  4979.1    0.07       0  5539.3   0.035       0
Bank Sta=4975.1,4979.1
Exp/Cntr=0.3,0.1

Type RM Length L Ch R = 1,1071,461,461,461
BEGIN DESCRIPTION:
Bitter Creek Trib16 1.0
END DESCRIPTION:
XS GIS Cut Line= 3
      1420955.04      6870637.99      1421204.91      6870553.39
      1421704.97      6870038.03
#Sta/Elev= 30
  4736.2 1969.80  4809.5 1967.77  4820.6 1962.34  4840.9 1958.82  4850.3 1953.08
  4850.5 1952.58  4854.3 1953.08  4877.6 1958.85  4909.0 1959.71  4917.0 1955.39
  4926.2 1956.05  4935.2 1953.94  4940.4 1959.24  4966.6 1954.80  4971.9 1958.20
  4989.5 1954.34  5003.9 1958.69  5010.9 1958.94  5018.1 1958.79  5025.0 1955.94
  5039.2 1956.11  5053.3 1959.02  5074.8 1956.03  5081.6 1959.67  5138.2 1966.31
  5159.5 1967.03  5272.5 1962.92  5322.1 1965.24  5520.7 1967.88  5718.1 1971.44
#Mann=6,-1,0
  4736.2    0.07       0  4850.3    0.07       0  4854.3    0.07       0
  4917.0    0.16       0  5074.8    0.07       0  5520.7   0.035       0
Bank Sta=4850.3,4854.3
Exp/Cntr=0.3,0.1

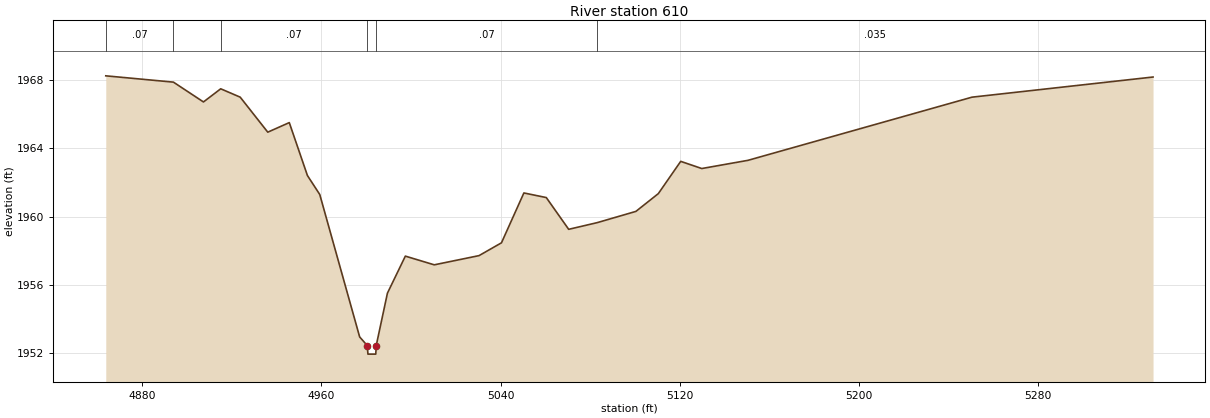
Type RM Length L Ch R = 1,610,0,0,0
BEGIN DESCRIPTION:
Bitter Creek Trib16 0.1
END DESCRIPTION:
XS GIS Cut Line= 3
      1420930.22      6870905.21      1421054.59      6870960.71
      1421385.75      6870966.35
#Sta/Elev= 30
  4863.8 1968.24  4894.0 1967.87  4907.4 1966.71  4915.1 1967.48  4923.8 1966.99
  4936.1 1964.94  4945.7 1965.50  4953.8 1962.40  4959.3 1961.29  4977.1 1952.95
  4980.5 1952.44  4980.8 1951.94  4984.3 1951.94  4984.5 1952.44  4989.5 1955.51
  4997.5 1957.68  5010.4 1957.17  5030.4 1957.71  5040.4 1958.46  5050.4 1961.38
  5060.4 1961.11  5070.4 1959.25  5083.1 1959.64  5100.4 1960.30  5110.4 1961.34
  5120.4 1963.23  5129.8 1962.81  5150.4 1963.29  5250.4 1966.99  5331.2 1968.17
#Mann=6,-1,0
  4863.8    0.07       0  4894.0    0.16       0  4915.1    0.07       0
  4980.5    0.07       0  4984.5    0.07       0  5083.1   0.035       0
Bank Sta=4980.5,4984.5
Exp/Cntr=0.3,0.1

Chan Stop Cuts=-1