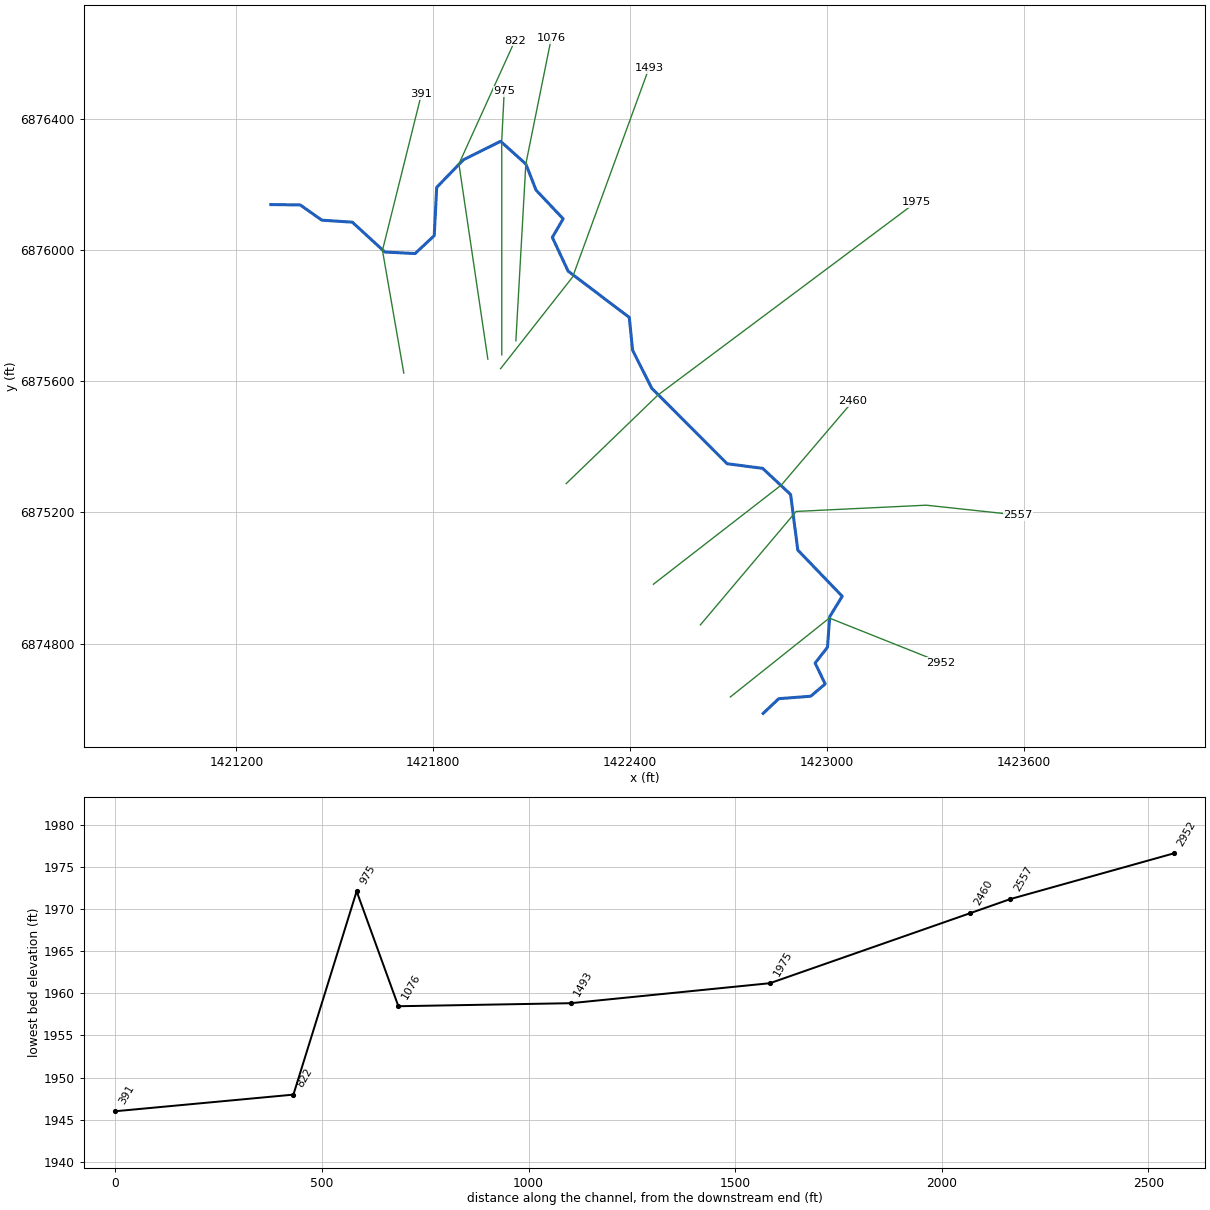
--- Bitter Creek Trib17.prj (project) ---

Proj Title=Bitter Creek Trib17 Base Level Engineering
Current Plan=p01
Default Exp/Contr=0.3,0.1
English Units
Geom File=g01
Flow File=f01
Plan File=p01
BEGIN DESCRIPTION:
Bitter Creek Trib17
END DESCRIPTION:

--- Bitter Creek Trib17.p01 (plan) ---

Plan Title=Multiple Run
Short Identifier=Multiple
Geom File=g01
Flow File=f01
Subcritical Flow
K Sum by GR= 0
Std Step Tol= 0.01
Critical Tol= 0.01
Num of Std Step Trials= 20
Max Error Tol= 0.3
Flow Tol Ratio= 0.001
Split Flow NTrial= 30
Split Flow Tol= 0.02
Split Flow Ratio= 0.02
Log Output Level= 0
Friction Slope Method= 1
Unsteady Friction Slope Method= 2
Unsteady Bridges Friction Slope Method= 1
Parabolic Critical Depth
Global Vel Dist=  1 , 1 , 1
Global Log Level= 0
CheckData=True
Encroach Param= -1, 0, 0, 0
BEGIN DESCRIPTION:
Multiple Run
END DESCRIPTION:

--- Bitter Creek Trib17.f01 (steady flow) ---

Flow Title=Multiple
Number of Profiles=7
Profile Names=10-year,25-year,50-year,1pct_min,100-year,1pct_plu,500-year
River Rch & RM= Bitter Creek Tri,Reach-1,2952
     108     144     173     104     207     413     298
Boundary for River Rch & Prof#=Bitter Creek Tri,Reach-1,1
Up Type=0
Dn Type=3
Dn Slope=0.005
Boundary for River Rch & Prof#=Bitter Creek Tri,Reach-1,2
Up Type=0
Dn Type=3
Dn Slope=0.005
Boundary for River Rch & Prof#=Bitter Creek Tri,Reach-1,3
Up Type=0
Dn Type=3
Dn Slope=0.005
Boundary for River Rch & Prof#=Bitter Creek Tri,Reach-1,4
Up Type=0
Dn Type=3
Dn Slope=0.005
Boundary for River Rch & Prof#=Bitter Creek Tri,Reach-1,5
Up Type=0
Dn Type=3
Dn Slope=0.005
Boundary for River Rch & Prof#=Bitter Creek Tri,Reach-1,6
Up Type=0
Dn Type=3
Dn Slope=0.005
Boundary for River Rch & Prof#=Bitter Creek Tri,Reach-1,7
Up Type=0
Dn Type=3
Dn Slope=0.005

--- Bitter Creek Trib17.g01 (geometry) ---

Geom Title=Existing Conditions

River Reach=Bitter Creek Tri,Reach-1
Reach XY= 30
      1422805.00      6874588.00      1422852.46      6874632.77
      1422949.94      6874640.23      1422993.92      6874677.63
      1422963.29      6874741.21      1423000.93      6874789.50
      1423007.68      6874882.52      1423045.87      6874944.74
      1422910.47      6875085.55      1422888.58      6875254.80
      1422803.52      6875334.39      1422695.21      6875348.52
      1422465.76      6875578.32      1422407.33      6875693.97
      1422397.15      6875794.19      1422210.70      6875935.46
      1422162.77      6876038.09      1422195.69      6876094.66
      1422113.20      6876181.95      1422081.99      6876261.57
      1422005.10      6876330.72      1421891.76      6876274.41
      1421810.46      6876190.46      1421802.91      6876043.24
      1421744.69      6875988.86      1421652.58      6875993.41
      1421553.50      6876084.38      1421460.56      6876090.45
      1421394.58      6876136.98      1421305.00      6876138.00

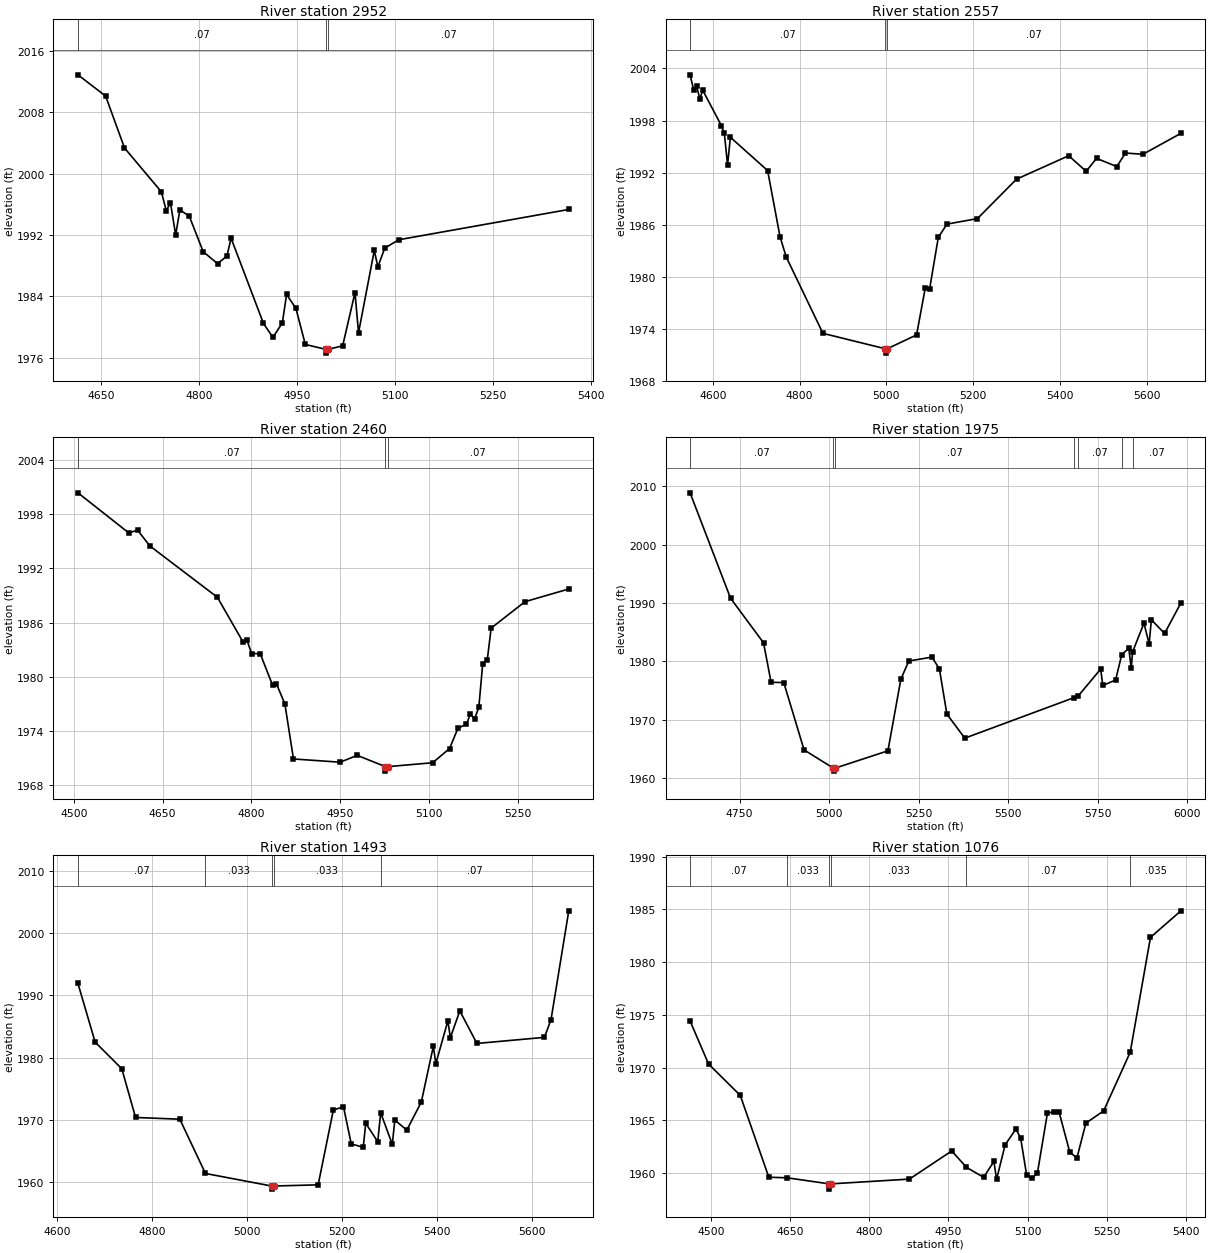
Type RM Length L Ch R = 1,2952,395,395,395
BEGIN DESCRIPTION:
Bitter Creek Trib17 3.0
END DESCRIPTION:
XS GIS Cut Line= 3
      1422705.01      6874638.01      1423006.66      6874878.36
      1423346.85      6874742.80
#Sta/Elev= 30
  4614.3 2012.89  4656.7 2010.12  4685.6 2003.35  4742.1 1997.63  4749.6 1995.16
  4756.0 1996.20  4764.0 1991.99  4770.4 1995.27  4784.8 1994.46  4806.1 1989.83
  4828.1 1988.26  4842.5 1989.25  4848.9 1991.58  4898.5 1980.46  4913.0 1978.64
  4927.4 1980.54  4933.9 1984.24  4948.2 1982.43  4962.6 1977.72  4993.7 1977.09
  4994.0 1976.59  4997.7 1977.09  5019.8 1977.54  5038.7 1984.48  5044.1 1979.24
  5068.3 1989.99  5073.7 1987.84  5084.3 1990.29  5105.9 1991.38  5366.2 1995.33
#Mann=3,-1,0
  4614.3    0.07       0  4993.7    0.07       0  4997.7    0.07       0
Bank Sta=4993.7,4997.7
Exp/Cntr=0.3,0.1

Type RM Length L Ch R = 1,2557,97,97,97
BEGIN DESCRIPTION:
Bitter Creek Trib17 2.1
END DESCRIPTION:
XS GIS Cut Line= 4
      1422613.78      6874857.63      1422905.45      6875203.19
      1423301.72      6875222.23      1423581.87      6875192.06
#Sta/Elev= 30
  4547.8 2003.27  4556.1 2001.55  4562.7 2001.98  4570.4 2000.50  4577.0 2001.49
  4619.9 1997.42  4626.8 1996.51  4634.2 1992.89  4640.7 1996.07  4726.5 1992.23
  4755.1 1984.59  4769.4 1982.26  4853.9 1973.46  4997.9 1971.68  4998.1 1971.18
  5001.9 1971.68  5069.6 1973.28  5089.7 1978.70  5099.7 1978.59  5119.7 1984.53
  5139.7 1986.06  5209.8 1986.69  5299.9 1991.24  5420.1 1993.94  5460.4 1992.14
  5484.2 1993.64  5530.8 1992.69  5550.9 1994.25  5591.1 1994.11  5678.5 1996.52
#Mann=3,-1,0
  4547.8    0.07       0  4997.9    0.07       0  5001.9    0.07       0
Bank Sta=4997.9,5001.9
Exp/Cntr=0.3,0.1

Type RM Length L Ch R = 1,2460,485,485,485
BEGIN DESCRIPTION:
Bitter Creek Trib17 2.0
END DESCRIPTION:
XS GIS Cut Line= 3
      1422470.54      6874981.33      1422860.63      6875283.86
      1423078.19      6875539.06
#Sta/Elev= 30
  4506.9 2000.39  4593.0 1995.93  4607.5 1996.26  4628.3 1994.50  4742.4 1988.80
  4785.8 1983.83  4792.2 1984.06  4800.3 1982.56  4814.8 1982.53  4835.6 1979.05
  4841.9 1979.23  4856.4 1976.97  4870.9 1970.86  4949.7 1970.50  4978.6 1971.26
  5026.1 1970.01  5026.3 1969.51  5030.1 1970.01  5106.0 1970.44  5134.6 1972.02
  5148.8 1974.28  5163.1 1974.71  5169.7 1975.87  5176.8 1975.30  5184.0 1976.60
  5190.5 1981.39  5198.3 1981.89  5204.8 1985.38  5261.9 1988.31  5335.9 1989.72
#Mann=3,-1,0
  4506.9    0.07       0  5026.1    0.07       0  5030.1    0.07       0
Bank Sta=5026.1,5030.1
Exp/Cntr=0.3,0.1

Type RM Length L Ch R = 1,1975,482,482,482
BEGIN DESCRIPTION:
Bitter Creek Trib17 1.0
END DESCRIPTION:
XS GIS Cut Line= 3
      1422204.99      6875287.99      1422484.61      6875557.84
      1423271.46      6876145.71
#Sta/Elev= 30
  4611.4 2008.89  4724.5 1990.83  4816.6 1983.19  4837.7 1976.43  4873.2 1976.37
  4929.8 1964.84  5011.9 1961.70  5012.2 1961.20  5015.9 1961.70  5164.0 1964.68
  5200.2 1976.97  5222.4 1980.07  5287.0 1980.74  5307.8 1978.71  5328.7 1970.97
  5378.7 1966.85  5684.1 1973.80  5696.0 1974.12  5758.1 1978.68  5764.3 1975.88
  5799.8 1976.81  5817.0 1981.14  5836.8 1982.27  5843.5 1978.84  5847.4 1981.64
  5879.0 1986.54  5893.6 1983.03  5899.8 1987.13  5936.7 1984.79  5982.2 1990.02
#Mann=7,-1,0
  4611.4    0.07       0  5011.9    0.07       0  5015.9    0.07       0
  5684.1   0.035       0  5696.0    0.07       0  5817.0   0.035       0
  5847.4    0.07       0
Bank Sta=5011.9,5015.9
Exp/Cntr=0.3,0.1

Type RM Length L Ch R = 1,1493,417,417,417
BEGIN DESCRIPTION:
Bitter Creek Trib17 0.3
END DESCRIPTION:
XS GIS Cut Line= 3
      1422004.99      6875637.99      1422224.62      6875917.53
      1422456.87      6876553.02
#Sta/Elev= 30
  4644.5 1991.92  4680.6 1982.49  4736.7 1978.20  4765.6 1970.36  4858.7 1970.08
  4912.6 1961.35  5051.7 1959.33  5052.0 1958.83  5055.7 1959.33  5149.6 1959.52
  5181.5 1971.54  5202.8 1972.10  5219.2 1966.10  5244.4 1965.57  5249.7 1969.42
  5274.9 1966.46  5281.1 1971.12  5305.5 1966.03  5310.8 1969.94  5336.0 1968.33
  5366.5 1972.84  5391.8 1981.81  5397.1 1979.02  5422.3 1985.90  5427.6 1983.21
  5447.5 1987.51  5483.4 1982.27  5625.4 1983.25  5639.3 1986.12  5676.6 2003.61
#Mann=5,-1,0
  4644.5    0.07       0  4912.6   0.033       0  5051.7   0.033       0
  5055.7   0.033       0  5281.1    0.07       0
Bank Sta=5051.7,5055.7
Exp/Cntr=0.3,0.1

Type RM Length L Ch R = 1,1076,101,101,101
BEGIN DESCRIPTION:
Bitter Creek Trib17 4108
END DESCRIPTION:
XS GIS Cut Line= 3
      1422051.66      6875723.03      1422081.99      6876261.57
      1422159.38      6876644.43
#Sta/Elev= 30
  4460.6 1974.42  4495.6 1970.34  4555.7 1967.36  4609.8 1959.60  4645.2 1959.54
  4724.0 1958.97  4724.2 1958.47  4728.0 1958.97  4876.2 1959.42  4956.4 1962.09
  4984.3 1960.54  5016.8 1959.59  5036.3 1961.09  5041.4 1959.40  5057.6 1962.67
  5078.0 1964.17  5087.0 1963.31  5098.4 1959.79  5108.6 1959.50  5118.8 1960.01
  5137.7 1965.66  5149.4 1965.81  5159.6 1965.82  5180.0 1961.99  5193.6 1961.42
  5210.6 1964.73  5244.3 1965.89  5294.6 1971.45  5333.0 1982.34  5390.6 1984.86
#Mann=6,-1,0
  4460.6    0.07       0  4645.2   0.033       0  4724.0    0.07       0
  4728.0   0.033       0  4984.3    0.07       0  5294.6   0.035       0
Bank Sta=4724,4728
Exp/Cntr=0.3,0.1

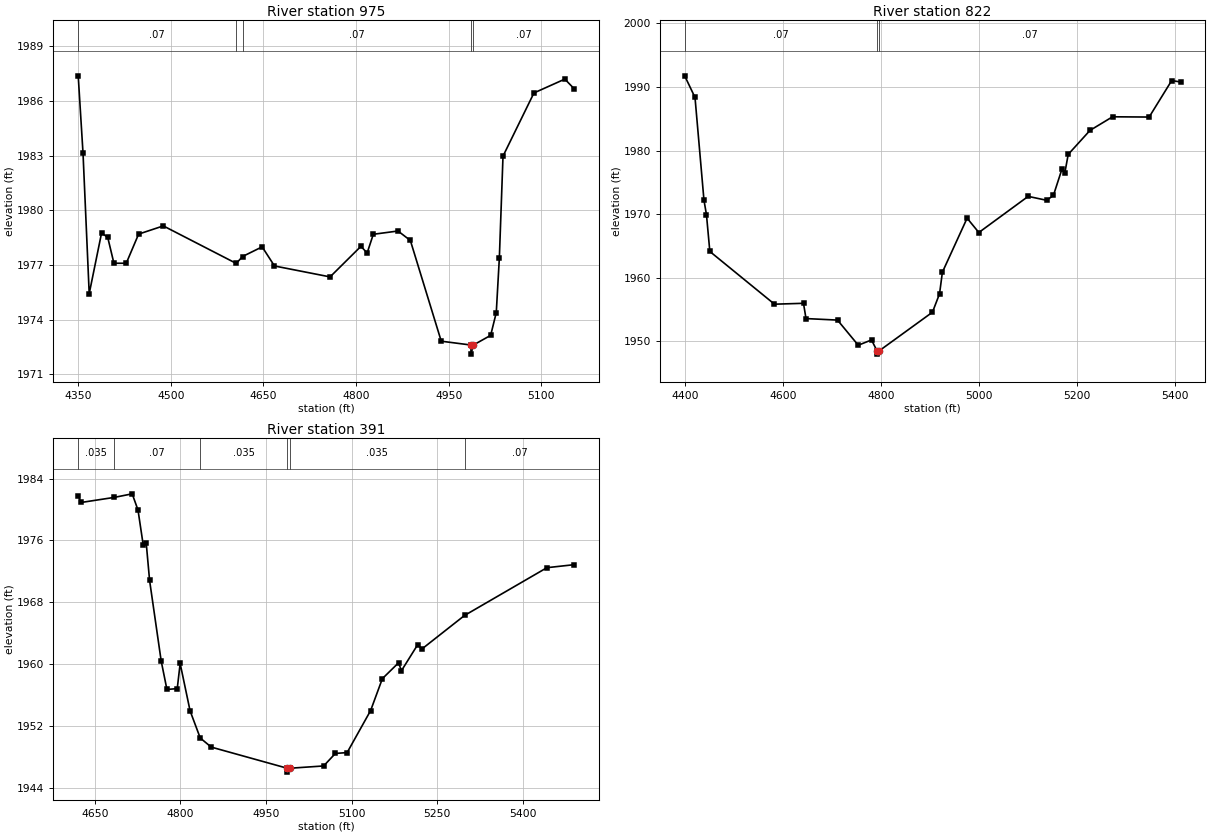
Type RM Length L Ch R = 1,975,153,153,153
BEGIN DESCRIPTION:
Bitter Creek Trib17 4169
END DESCRIPTION:
XS GIS Cut Line= 4
      1422008.67      6875680.24      1422008.67      6876279.20
      1422008.42      6876330.24      1422016.22      6876483.04
#Sta/Elev= 30
  4350.0 1987.38  4357.8 1983.12  4367.8 1975.42  4387.8 1978.75  4397.8 1978.51
  4407.8 1977.09  4427.8 1977.09  4447.8 1978.69  4487.8 1979.14  4605.9 1977.08
  4616.1 1977.46  4647.8 1977.99  4667.8 1976.94  4757.8 1976.34  4807.8 1978.02
  4817.8 1977.65  4827.8 1978.68  4867.8 1978.86  4887.8 1978.34  4937.8 1972.81
  4985.8 1972.60  4986.0 1972.10  4989.8 1972.60  5017.8 1973.13  5026.9 1974.38
  5031.9 1977.39  5037.8 1982.97  5087.9 1986.44  5137.9 1987.20  5153.0 1986.67
#Mann=5,-1,0
  4350.0    0.07       0  4605.9   0.033       0  4616.1    0.07       0
  4985.8    0.07       0  4989.8    0.07       0
Bank Sta=4985.8,4989.8
Exp/Cntr=0.3,0.1

Type RM Length L Ch R = 1,822,431,431,431
BEGIN DESCRIPTION:
Bitter Creek Trib17 0.2
END DESCRIPTION:
XS GIS Cut Line= 3
      1421966.25      6875667.14      1421878.11      6876261.74
      1422048.64      6876637.12
#Sta/Elev= 30
  4398.9 1991.74  4420.0 1988.34  4438.3 1972.19  4443.4 1969.92  4450.3 1964.13
  4582.4 1955.84  4641.7 1955.98  4646.8 1953.58  4711.2 1953.34  4753.6 1949.39
  4780.7 1950.22  4792.0 1948.49  4792.3 1947.99  4796.0 1948.49  4905.2 1954.58
  4919.7 1957.48  4925.5 1960.87  4976.0 1969.36  5000.0 1967.11  5100.8 1972.79
  5138.7 1972.17  5152.4 1972.95  5170.0 1977.12  5175.5 1976.40  5182.6 1979.39
  5227.1 1983.16  5273.2 1985.30  5348.0 1985.26  5394.1 1991.00  5412.3 1990.77
#Mann=3,-1,0
  4398.9    0.07       0  4792.0    0.07       0  4796.0    0.07       0
Bank Sta=4792,4796
Exp/Cntr=0.3,0.1

Type RM Length L Ch R = 1,391,0,0,0
BEGIN DESCRIPTION:
Bitter Creek Trib17 0.1
END DESCRIPTION:
XS GIS Cut Line= 3
      1421710.26      6875624.67      1421645.23      6875998.46
      1421763.91      6876474.38
#Sta/Elev= 30
  4620.6 1981.76  4625.6 1980.92  4684.0 1981.58  4715.3 1982.04  4725.5 1979.93
  4734.7 1975.38  4739.8 1975.74  4745.8 1970.83  4766.1 1960.42  4776.2 1956.72
  4794.3 1956.83  4799.4 1960.08  4816.8 1953.96  4834.6 1950.44  4853.9 1949.26
  4987.4 1946.52  4987.6 1946.02  4991.4 1946.52  5051.1 1946.82  5071.7 1948.44
  5092.3 1948.55  5133.5 1953.99  5154.1 1958.12  5182.5 1960.17  5187.6 1959.15
  5216.0 1962.51  5223.7 1961.97  5298.3 1966.30  5442.7 1972.48  5490.5 1972.87
#Mann=6,-1,0
  4620.6   0.035       0  4684.0    0.07       0  4834.6   0.035       0
  4987.4   0.035       0  4991.4   0.035       0  5298.3    0.07       0
Bank Sta=4987.4,4991.4
Exp/Cntr=0.3,0.1

Chan Stop Cuts=-1