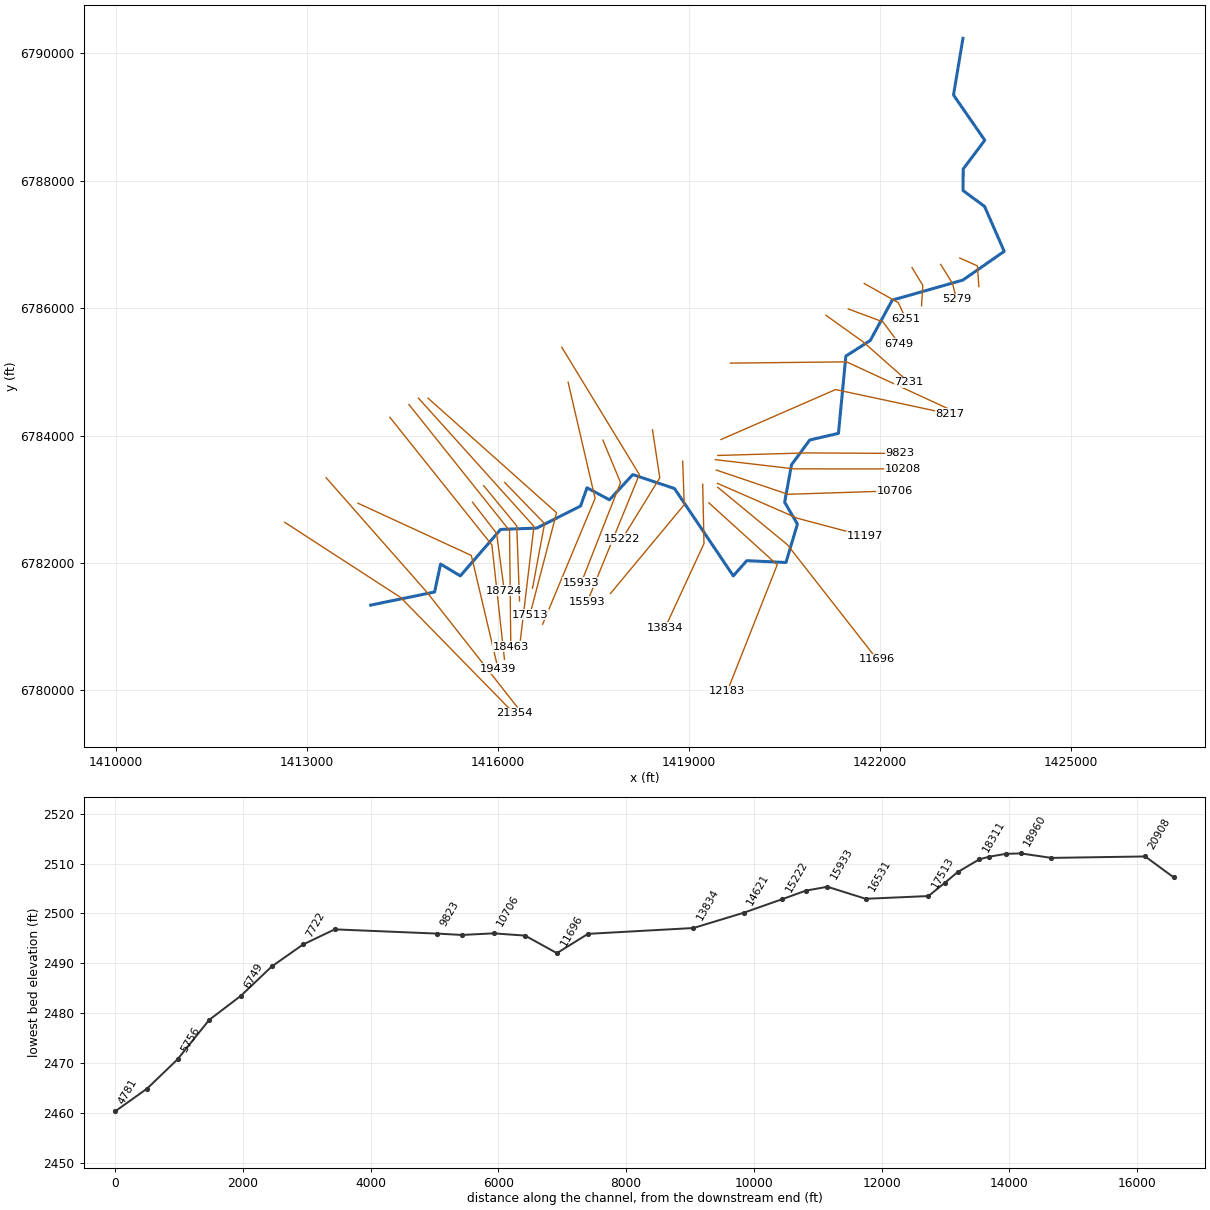
--- Bitter Creek Trib1T2.prj (project) ---

Proj Title=Bitter Creek Trib1T2 Base Level Engineering
Current Plan=p01
Default Exp/Contr=0.3,0.1
English Units
Geom File=g01
Flow File=f01
Plan File=p01
BEGIN DESCRIPTION:
Bitter Creek Trib1T2
END DESCRIPTION:

--- Bitter Creek Trib1T2.p01 (plan) ---

Plan Title=Multiple Run
Short Identifier=Multiple
Geom File=g01
Flow File=f01
Subcritical Flow
K Sum by GR= 0
Std Step Tol= 0.01
Critical Tol= 0.01
Num of Std Step Trials= 20
Max Error Tol= 0.3
Flow Tol Ratio= 0.001
Split Flow NTrial= 30
Split Flow Tol= 0.02
Split Flow Ratio= 0.02
Log Output Level= 0
Friction Slope Method= 1
Unsteady Friction Slope Method= 2
Unsteady Bridges Friction Slope Method= 1
Parabolic Critical Depth
Global Vel Dist=  1 , 1 , 1
Global Log Level= 0
CheckData=True
Encroach Param= -1, 0, 0, 0
BEGIN DESCRIPTION:
Multiple Run
END DESCRIPTION:

--- Bitter Creek Trib1T2.f01 (steady flow) ---

Flow Title=Multiple
Number of Profiles=7
Profile Names=10-year,25-year,50-year,1pct_min,100-year,1pct_plu,500-year
River Rch & RM= Bitter Creek Tri,Reach-1,21354
     205     275     330     196     392     781     560
River Rch & RM= Bitter Creek Tri,Reach-1,12183
     237     316     379     224     448     893     635
River Rch & RM= Bitter Creek Tri,Reach-1,6749
     250     335     402     239     476     949     677
River Rch & RM= Bitter Creek Tri,Reach-1,4384
     563     802    1002     620    1237    2468    1909
Boundary for River Rch & Prof#=Bitter Creek Tri,Reach-1,1
Up Type=0
Dn Type=3
Dn Slope=0.005
Boundary for River Rch & Prof#=Bitter Creek Tri,Reach-1,2
Up Type=0
Dn Type=3
Dn Slope=0.005
Boundary for River Rch & Prof#=Bitter Creek Tri,Reach-1,3
Up Type=0
Dn Type=3
Dn Slope=0.005
Boundary for River Rch & Prof#=Bitter Creek Tri,Reach-1,4
Up Type=0
Dn Type=3
Dn Slope=0.005
Boundary for River Rch & Prof#=Bitter Creek Tri,Reach-1,5
Up Type=0
Dn Type=3
Dn Slope=0.005
Boundary for River Rch & Prof#=Bitter Creek Tri,Reach-1,6
Up Type=0
Dn Type=3
Dn Slope=0.005
Boundary for River Rch & Prof#=Bitter Creek Tri,Reach-1,7
Up Type=0
Dn Type=3
Dn Slope=0.005

--- Bitter Creek Trib1T2.g01 (geometry) ---

Geom Title=Existing Conditions

River Reach=Bitter Creek Tri,Reach-1
Reach XY= 30
      1414005.00      6781338.00      1415007.45      6781543.46
      1415102.46      6781983.04      1415412.06      6781796.97
      1416045.00      6782526.77      1416611.55      6782547.25
      1417299.92      6782893.04      1417401.57      6783180.61
      1417753.75      6782991.36      1418120.16      6783387.62
      1418775.42      6783168.23      1419698.45      6781796.89
      1419910.45      6782035.84      1420525.75      6782007.47
      1420705.21      6782610.65      1420504.89      6782953.21
      1420612.77      6783541.41      1420898.61      6783930.65
      1421349.88      6784035.17      1421466.11      6785248.32
      1421849.56      6785493.25      1422194.62      6786127.04
      1423303.50      6786441.61      1423952.83      6786893.45
      1423643.89      6787598.32      1423306.04      6787848.44
      1423308.68      6788186.41      1423647.68      6788637.90
      1423156.36      6789347.65      1423305.00      6790238.00

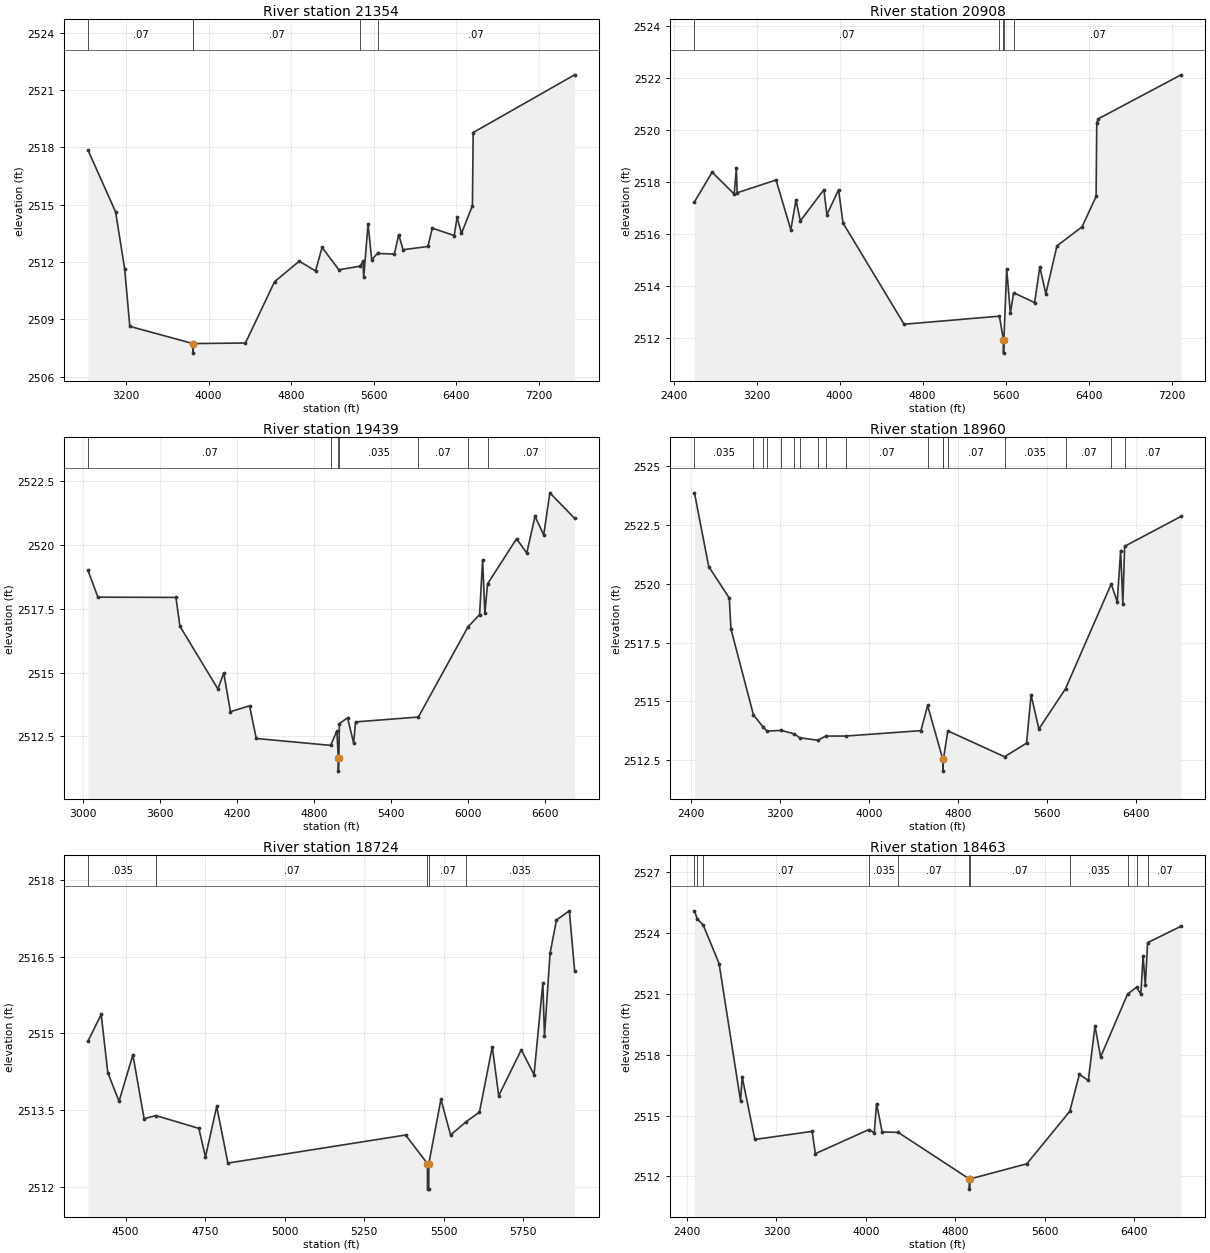
Type RM Length L Ch R = 1,21354,446,446,446
BEGIN DESCRIPTION:
Bitter Creek Trib1T2 32.0
END DESCRIPTION:
XS GIS Cut Line= 3
      1412655.01      6782637.99      1414474.98      6781458.04
      1416255.01      6779637.99
#Sta/Elev= 30
  2831.0 2517.86  3098.3 2514.63  3186.0 2511.66  3236.2 2508.64  3848.6 2507.74
  3848.8 2507.24  3852.6 2507.74  4356.5 2507.77  4639.1 2510.98  4877.7 2512.05
  5035.4 2511.54  5099.0 2512.77  5261.7 2511.60  5467.3 2511.79  5495.0 2512.04
  5502.2 2511.20  5544.6 2514.01  5579.9 2512.13  5636.1 2512.46  5799.1 2512.42
  5841.5 2513.44  5883.9 2512.65  6124.4 2512.82  6166.8 2513.78  6379.0 2513.39
  6407.3 2514.34  6449.7 2513.50  6555.7 2514.96  6562.9 2518.78  7545.8 2521.80
#Mann=5,-1,0
  2831.0    0.07       0  3848.6    0.07       0  3852.6    0.07       0
  5467.3   0.035       0  5636.1    0.07       0
Bank Sta=3848.6,3852.6
Exp/Cntr=0.3,0.1

Type RM Length L Ch R = 1,20908,1469,1469,1469
BEGIN DESCRIPTION:
Bitter Creek Trib1T2 31.0
END DESCRIPTION:
XS GIS Cut Line= 3
      1413305.01      6783337.98      1414890.02      6781537.96
      1416304.97      6779738.04
#Sta/Elev= 30
  2601.6 2517.24  2771.9 2518.38  2984.4 2517.54  3005.3 2518.54  3012.8 2517.59
  3387.7 2518.08  3529.9 2516.17  3579.2 2517.31  3621.9 2516.51  3848.7 2517.71
  3877.1 2516.75  3990.1 2517.70  4032.7 2516.43  4620.9 2512.54  5539.2 2512.85
  5578.5 2511.93  5578.8 2511.43  5582.6 2511.93  5609.5 2514.66  5644.8 2512.97
  5676.4 2513.75  5878.9 2513.37  5928.6 2514.75  5986.4 2513.71  6093.9 2515.55
  6335.5 2516.28  6470.8 2517.45  6477.1 2520.28  6491.6 2520.43  7289.5 2522.12
#Mann=5,-1,0
  2601.6    0.07       0  5539.2   0.035       0  5578.5    0.07       0
  5582.6   0.035       0  5676.4    0.07       0
Bank Sta=5578.5,5582.6
Exp/Cntr=0.3,0.1

Type RM Length L Ch R = 1,19439,479,479,479
BEGIN DESCRIPTION:
Bitter Creek Trib1T2 30.0
END DESCRIPTION:
XS GIS Cut Line= 3
      1413804.96      6782938.02      1415584.96      6782118.02
      1416005.00      6780338.01
#Sta/Elev= 30
  3040.2 2519.01  3117.3 2517.96  3724.9 2517.95  3755.9 2516.82  4051.8 2514.36
  4097.2 2514.99  4149.2 2513.47  4297.9 2513.70  4350.4 2512.42  4929.3 2512.15
  4978.0 2512.72  4989.1 2511.64  4989.4 2511.14  4993.5 2511.64  4997.3 2513.00
  5061.0 2513.23  5108.5 2512.24  5123.3 2513.07  5612.3 2513.26  5998.2 2516.79
  6089.1 2517.28  6112.6 2519.42  6130.2 2517.32  6151.0 2518.48  6376.8 2520.25
  6456.3 2519.69  6520.7 2521.13  6588.4 2520.40  6635.9 2522.05  6828.9 2521.05
#Mann=7,-1,0
  3040.2    0.07       0  4929.3   0.035       0  4989.1   0.035       0
  4993.5   0.035       0  5612.3    0.07       0  5998.2   0.035       0
  6151.0    0.07       0
Bank Sta=4989.1,4993.5
Exp/Cntr=0.3,0.1

Type RM Length L Ch R = 1,18960,236,236,236
BEGIN DESCRIPTION:
Bitter Creek Trib1T2 29.0
END DESCRIPTION:
XS GIS Cut Line= 3
      1414304.98      6784288.03      1415907.93      6782281.87
      1416105.00      6780487.96
#Sta/Elev= 30
  2432.1 2523.86  2560.1 2520.73  2745.1 2519.39  2759.5 2518.09  2962.0 2514.43
  3047.9 2513.92  3084.7 2513.74  3212.4 2513.77  3330.0 2513.62  3376.8 2513.46
  3541.3 2513.35  3611.5 2513.53  3790.6 2513.53  4467.3 2513.76  4526.8 2514.83
  4664.1 2512.54  4664.4 2512.04  4668.6 2512.54  4708.6 2513.75  5218.8 2512.65
  5416.4 2513.23  5456.6 2515.28  5527.0 2513.83  5766.4 2515.54  6177.1 2519.99
  6231.2 2519.23  6261.4 2521.41  6281.5 2519.15  6297.7 2521.59  6804.7 2522.86
#Mann=18,-1,0
  2432.1   0.035       0  2962.0   0.063       0  3047.9   0.035       0
  3084.7   0.063       0  3212.4   0.035       0  3330.0   0.063       0
  3376.8   0.035       0  3541.3    0.07       0  3611.5   0.035       0
  3790.6    0.07       0  4526.8   0.035       0  4664.1    0.07       0
  4668.6   0.035       0  4708.6    0.07       0  5218.8   0.035       0
  5766.4    0.07       0  6177.1   0.035       0  6297.7    0.07       0
Bank Sta=4664.1,4668.6
Exp/Cntr=0.3,0.1

Type RM Length L Ch R = 1,18724,261,261,261
BEGIN DESCRIPTION:
Bitter Creek Trib1T2 28.1
END DESCRIPTION:
XS GIS Cut Line= 3
      1415603.08      6782953.84      1415981.56      6782464.80
      1416102.95      6781561.52
#Sta/Elev= 30
  4381.6 2514.85  4423.1 2515.37  4443.9 2514.23  4479.2 2513.67  4522.7 2514.58
  4558.0 2513.33  4595.3 2513.39  4730.1 2513.14  4750.9 2512.58  4786.2 2513.57
  4821.5 2512.46  5380.2 2513.01  5448.6 2512.45  5448.9 2511.95  5452.8 2511.95
  5453.1 2512.45  5491.2 2513.71  5521.4 2513.01  5570.5 2513.27  5612.3 2513.46
  5652.6 2514.74  5672.8 2513.78  5743.8 2514.68  5783.8 2514.19  5811.6 2515.99
  5816.6 2514.95  5834.2 2516.57  5854.4 2517.22  5894.8 2517.40  5911.4 2516.23
#Mann=5,-1,0
  4381.6   0.035       0  4595.3    0.07       0  5448.6    0.07       0
  5453.1    0.07       0  5570.5   0.035       0
Bank Sta=5448.6,5453.1
Exp/Cntr=0.3,0.1

Type RM Length L Ch R = 1,18463,152,152,152
BEGIN DESCRIPTION:
Bitter Creek Trib1T2 28.0
END DESCRIPTION:
XS GIS Cut Line= 3
      1414604.97      6784488.03      1416185.00      6782508.11
      1416205.00      6780688.02
#Sta/Elev= 30
  2466.9 2525.10  2492.5 2524.70  2545.0 2524.40  2687.1 2522.50  2879.3 2515.72
  2893.7 2516.90  3007.4 2513.82  3519.7 2514.22  3548.6 2513.12  4027.6 2514.31
  4075.4 2514.15  4096.2 2515.59  4145.8 2514.19  4289.5 2514.17  4926.6 2511.87
  4926.9 2511.37  4931.1 2511.87  5440.1 2512.62  5824.5 2515.21  5910.2 2517.03
  5990.2 2516.73  6050.2 2519.42  6100.2 2517.89  6341.4 2520.99  6422.0 2521.33
  6460.2 2520.99  6480.2 2522.88  6500.2 2521.43  6520.8 2523.53  6820.2 2524.34
#Mann=11,-1,0
  2466.9    0.07       0  2492.5   0.035       0  2545.0    0.07       0
  4027.6   0.035       0  4289.5    0.07       0  4926.6    0.07       0
  4931.1    0.07       0  5824.5   0.035       0  6341.4    0.07       0
  6422.0   0.035       0  6520.8    0.07       0
Bank Sta=4926.6,4931.1
Exp/Cntr=0.3,0.1

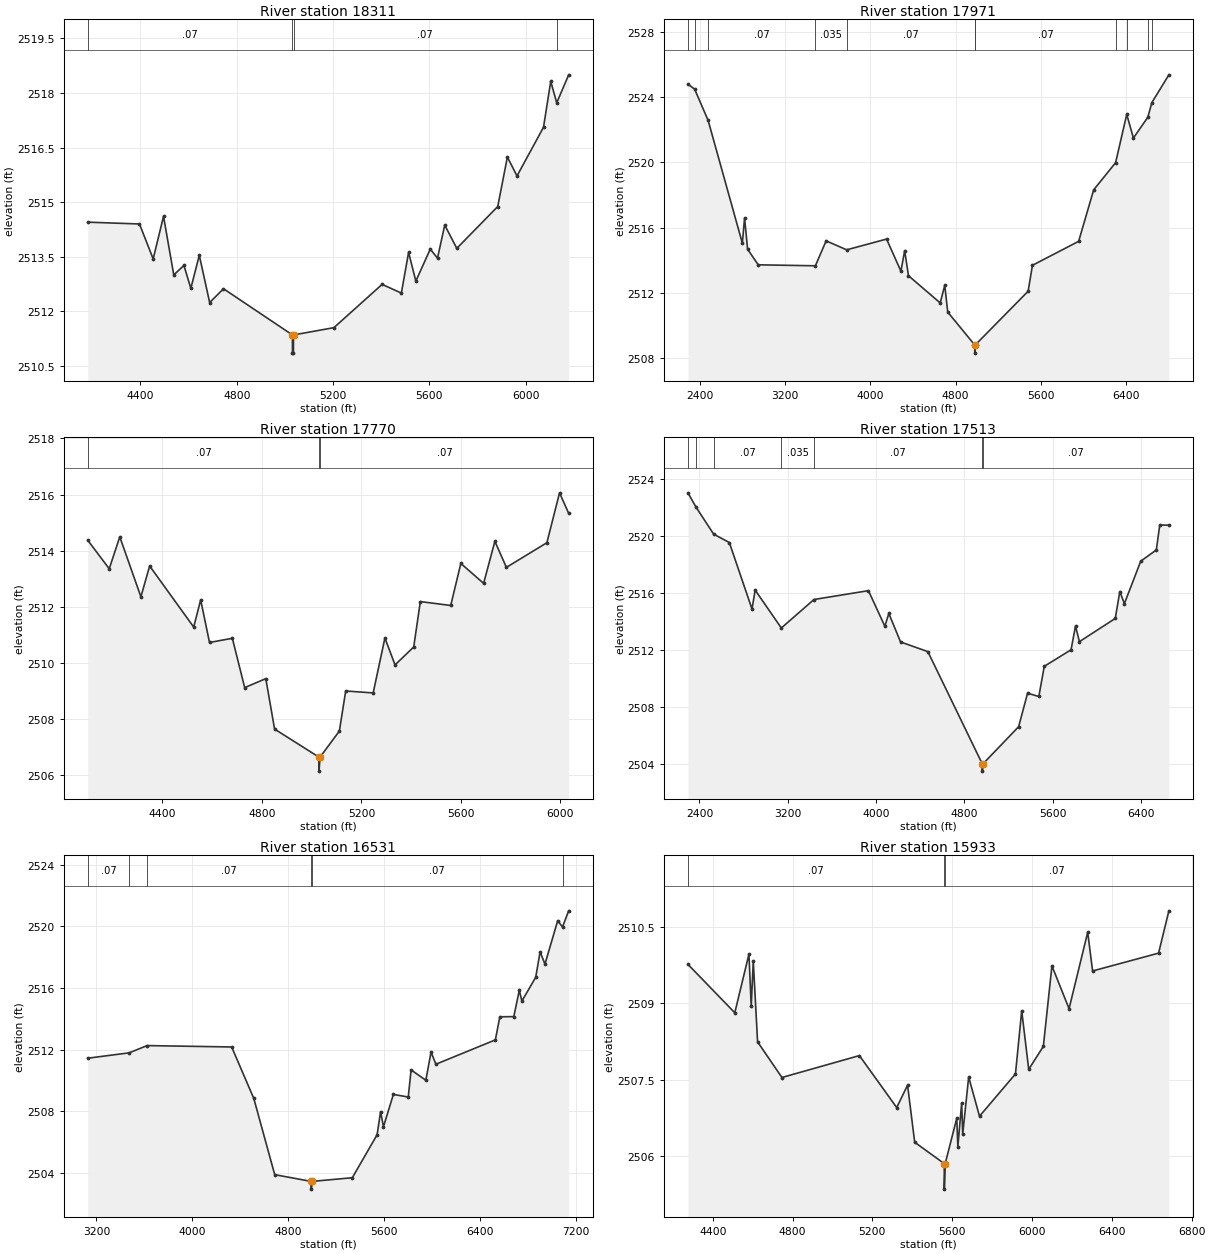
Type RM Length L Ch R = 1,18311,340,340,340
BEGIN DESCRIPTION:
Bitter Creek Trib1T2 27.1
END DESCRIPTION:
XS GIS Cut Line= 3
      1415778.19      6783214.04      1416298.27      6782581.49
      1416341.78      6781403.69
#Sta/Elev= 30
  4181.1 2514.45  4396.1 2514.40  4453.0 2513.44  4496.0 2514.61  4538.5 2513.00
  4580.7 2513.26  4609.4 2512.63  4644.5 2513.54  4687.6 2512.24  4745.0 2512.62
  5031.3 2511.35  5031.6 2510.85  5035.5 2510.85  5035.8 2511.35  5203.6 2511.55
  5403.8 2512.74  5483.8 2512.50  5513.8 2513.62  5543.9 2512.83  5603.9 2513.71
  5633.9 2513.46  5663.9 2514.37  5714.0 2513.73  5884.1 2514.88  5924.1 2516.24
  5964.1 2515.72  6074.2 2517.06  6104.2 2518.32  6129.1 2517.73  6178.6 2518.50
#Mann=4,-1,0
  4181.1    0.07       0  5031.3    0.07       0  5035.8    0.07       0
  6129.1   0.035       0
Bank Sta=5031.3,5035.8
Exp/Cntr=0.3,0.1

Type RM Length L Ch R = 1,17971,201,201,201
BEGIN DESCRIPTION:
Bitter Creek Trib1T2 27.0
END DESCRIPTION:
XS GIS Cut Line= 3
      1414754.99      6784588.01      1416568.32      6782574.08
      1416355.00      6780787.97
#Sta/Elev= 30
  2290.0 2524.80  2353.0 2524.49  2479.4 2522.57  2800.1 2515.04  2821.0 2516.59
  2849.4 2514.67  2948.9 2513.71  3485.0 2513.65  3585.6 2515.18  3778.3 2514.63
  4152.2 2515.29  4286.7 2513.32  4321.9 2514.58  4357.7 2513.04  4655.2 2511.37
  4697.8 2512.46  4725.6 2510.81  4978.8 2508.79  4979.1 2508.29  4983.3 2508.79
  5479.5 2512.09  5519.7 2513.68  5952.8 2515.15  6093.8 2518.31  6299.4 2519.98
  6403.8 2522.94  6466.4 2521.49  6601.7 2522.77  6639.6 2523.67  6798.8 2525.37
#Mann=11,-1,0
  2290.0    0.07       0  2353.0   0.035       0  2479.4    0.07       0
  3485.0   0.035       0  3778.3    0.07       0  4978.8    0.07       0
  4983.3    0.07       0  6299.4   0.035       0  6403.8   0.063       0
  6601.7   0.035       0  6639.6    0.07       0
Bank Sta=4978.8,4983.3
Exp/Cntr=0.3,0.1

Type RM Length L Ch R = 1,17770,257,257,257
BEGIN DESCRIPTION:
Bitter Creek Trib1T2 26.1
END DESCRIPTION:
XS GIS Cut Line= 3
      1416108.61      6783263.83      1416735.16      6782617.61
      1416545.41      6781601.98
#Sta/Elev= 30
  4099.9 2514.37  4186.4 2513.35  4228.8 2514.49  4313.7 2512.35  4348.9 2513.45
  4525.9 2511.27  4554.0 2512.24  4589.5 2510.72  4681.3 2510.87  4730.9 2509.11
  4815.8 2509.43  4851.1 2507.63  5029.4 2506.63  5029.7 2506.13  5033.9 2506.63
  5111.5 2507.56  5137.0 2508.99  5247.4 2508.92  5294.6 2510.88  5335.3 2509.92
  5410.4 2510.56  5437.0 2512.18  5559.1 2512.04  5599.8 2513.54  5691.4 2512.83
  5736.6 2514.33  5782.9 2513.40  5945.7 2514.28  5996.6 2516.06  6033.2 2515.33
#Mann=3,-1,0
  4099.9    0.07       0  5029.4    0.07       0  5033.9    0.07       0
Bank Sta=5029.4,5033.9
Exp/Cntr=0.3,0.1

Type RM Length L Ch R = 1,17513,982,982,982
BEGIN DESCRIPTION:
Bitter Creek Trib1T2 26.0
END DESCRIPTION:
XS GIS Cut Line= 3
      1414905.01      6784587.99      1416923.41      6782787.59
      1416505.00      6781188.00
#Sta/Elev= 30
  2295.3 2523.03  2368.4 2522.03  2528.3 2520.13  2670.5 2519.54  2875.9 2514.87
  2904.4 2516.20  3141.7 2513.54  3437.6 2515.54  3931.0 2516.16  4079.8 2513.66
  4115.8 2514.56  4222.0 2512.56  4469.4 2511.88  4963.0 2503.99  4963.3 2503.49
  4967.5 2503.99  5292.1 2506.61  5373.0 2508.96  5475.0 2508.73  5524.4 2510.85
  5767.0 2512.01  5807.4 2513.68  5842.7 2512.58  6167.6 2514.21  6208.9 2516.10
  6250.3 2515.25  6398.4 2518.23  6539.7 2519.02  6570.7 2520.77  6653.4 2520.76
#Mann=7,-1,0
  2295.3    0.07       0  2368.4   0.035       0  2528.3    0.07       0
  3141.7   0.035       0  3437.6    0.07       0  4963.0    0.07       0
  4967.5    0.07       0
Bank Sta=4963,4967.5
Exp/Cntr=0.3,0.1

Type RM Length L Ch R = 1,16531,598,598,598
BEGIN DESCRIPTION:
Bitter Creek Trib1T2 25.0
END DESCRIPTION:
XS GIS Cut Line= 3
      1417105.00      6784837.99      1417528.27      6783013.75
      1416705.00      6781038.01
#Sta/Elev= 30
  3127.3 2511.44  3473.4 2511.79  3622.9 2512.26  4328.4 2512.17  4513.1 2508.83
  4687.7 2503.88  4992.9 2503.44  4993.3 2502.94  4997.6 2503.44  5335.1 2503.68
  5542.0 2506.47  5571.2 2507.97  5595.1 2506.99  5677.9 2509.09  5802.0 2508.92
  5825.8 2510.68  5948.7 2510.01  5992.1 2511.84  6032.7 2511.05  6528.9 2512.63
  6566.2 2514.13  6682.7 2514.14  6728.7 2515.85  6750.4 2515.15  6865.8 2516.70
  6902.1 2518.35  6942.7 2517.55  7048.9 2520.37  7089.1 2519.96  7140.4 2521.01
#Mann=6,-1,0
  3127.3    0.07       0  3473.4   0.094       0  3622.9    0.07       0
  4992.9    0.07       0  4997.6    0.07       0  7089.1   0.035       0
Bank Sta=4992.9,4997.6
Exp/Cntr=0.3,0.1

Type RM Length L Ch R = 1,15933,340,340,340
BEGIN DESCRIPTION:
Bitter Creek Trib1T2 24.1
END DESCRIPTION:
XS GIS Cut Line= 3
      1417650.04      6783930.26      1417928.18      6783261.71
      1417312.12      6781692.50
#Sta/Elev= 30
  4275.9 2509.76  4510.7 2508.81  4581.6 2509.96  4593.0 2508.94  4603.3 2509.82
  4624.9 2508.24  4746.9 2507.54  5135.1 2507.97  5322.1 2506.95  5376.4 2507.39
  5412.2 2506.27  5560.3 2505.85  5560.6 2505.35  5565.0 2505.85  5623.0 2506.74
  5628.4 2506.18  5647.5 2507.04  5652.8 2506.43  5682.6 2507.55  5736.9 2506.78
  5917.1 2507.61  5948.4 2508.85  5983.5 2507.70  6056.8 2508.15  6099.8 2509.73
  6185.7 2508.89  6279.1 2510.39  6303.5 2509.63  6634.2 2509.98  6685.8 2510.81
#Mann=3,-1,0
  4275.9    0.07       0  5560.3    0.07       0  5565.0    0.07       0
Bank Sta=5560.3,5565
Exp/Cntr=0.3,0.1

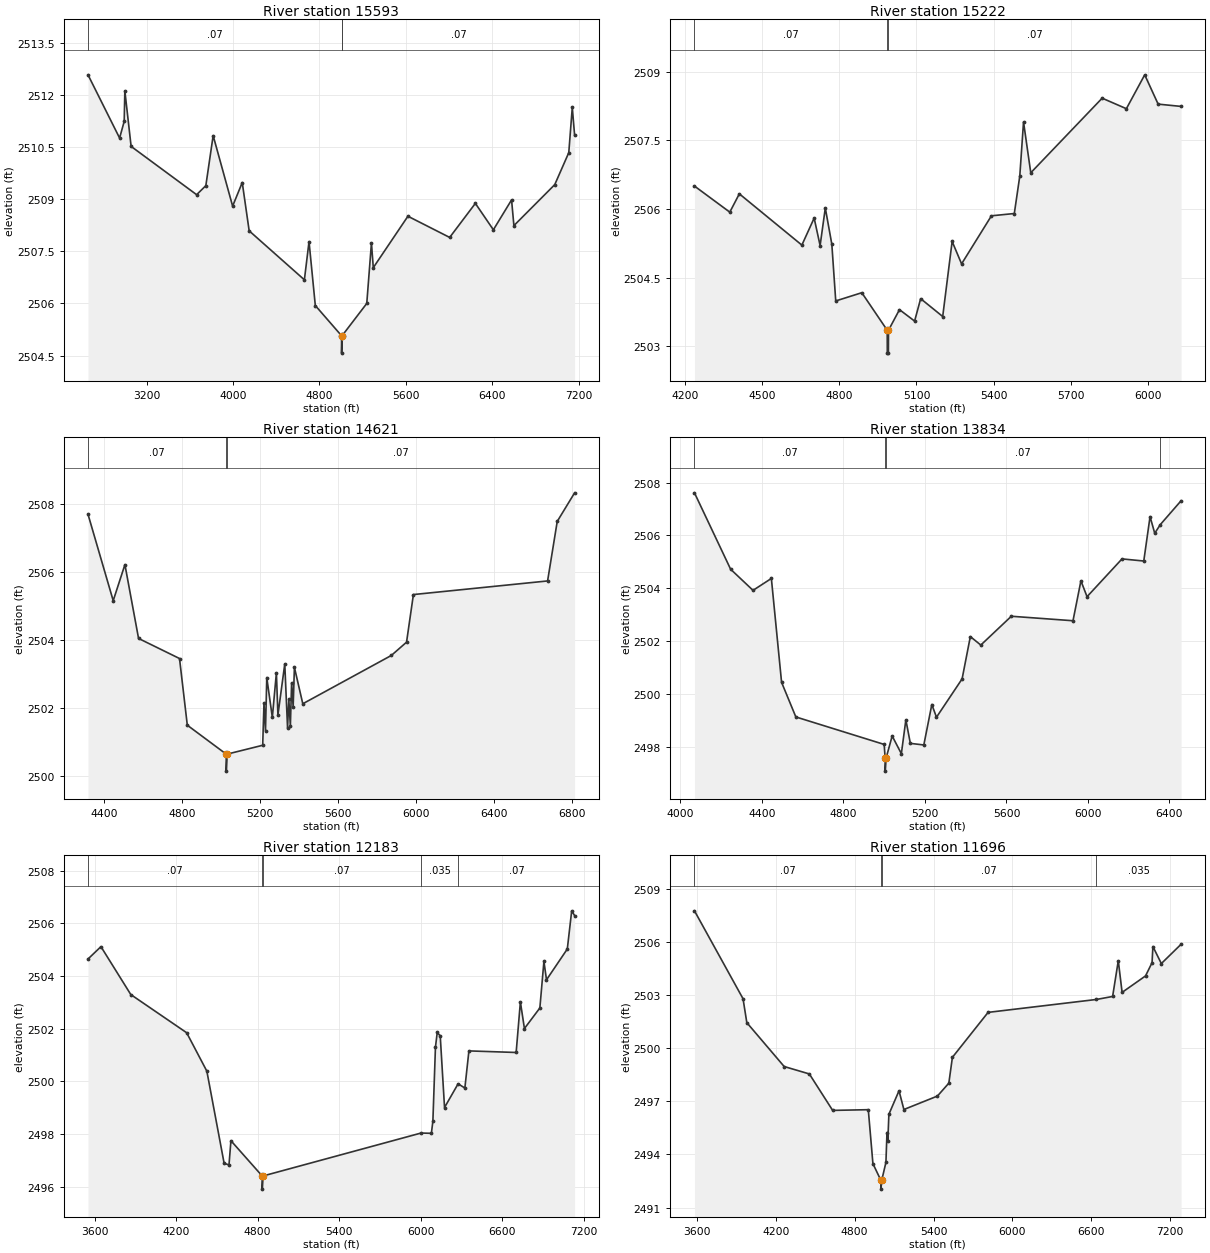
Type RM Length L Ch R = 1,15593,371,371,371
BEGIN DESCRIPTION:
Bitter Creek Trib1T2 24.0
END DESCRIPTION:
XS GIS Cut Line= 3
      1417005.02      6785387.96      1418223.24      6783388.20
      1417405.00      6781387.99
#Sta/Elev= 30
  2658.4 2512.58  2950.8 2510.76  2993.4 2511.24  2999.3 2512.12  3057.4 2510.52
  3663.5 2509.13  3748.8 2509.39  3816.5 2510.83  3996.7 2508.80  4085.7 2509.48
  4149.7 2508.09  4660.7 2506.68  4703.6 2507.78  4761.7 2505.94  5004.7 2505.07
  5005.0 2504.57  5009.4 2505.07  5237.9 2506.00  5281.1 2507.74  5298.2 2507.03
  5618.7 2508.51  6005.0 2507.90  6242.7 2508.88  6409.3 2508.12  6577.7 2508.98
  6599.3 2508.24  6977.4 2509.42  7107.1 2510.34  7139.5 2511.64  7161.1 2510.84
#Mann=3,-1,0
  2658.4    0.07       0  5004.7    0.07       0  5009.4    0.07       0
Bank Sta=5004.7,5009.4
Exp/Cntr=0.3,0.1

Type RM Length L Ch R = 1,15222,601,601,601
BEGIN DESCRIPTION:
Bitter Creek Trib1T2 23.2
END DESCRIPTION:
XS GIS Cut Line= 3
      1418429.55      6784090.23      1418544.51      6783337.05
      1417953.25      6782377.14
#Sta/Elev= 30
  4238.1 2506.50  4375.3 2505.93  4412.3 2506.33  4655.1 2505.21  4702.8 2505.80
  4725.9 2505.20  4746.1 2506.02  4771.4 2505.23  4786.6 2503.99  4887.8 2504.17
  4986.5 2503.35  4986.8 2502.85  4991.0 2502.85  4991.4 2503.35  5034.1 2503.80
  5092.8 2503.55  5116.3 2504.04  5201.9 2503.65  5238.5 2505.29  5275.2 2504.80
  5391.1 2505.85  5479.9 2505.90  5501.2 2506.72  5515.7 2507.90  5543.8 2506.79
  5821.0 2508.42  5915.0 2508.19  5986.2 2508.93  6038.3 2508.29  6127.4 2508.24
#Mann=3,-1,0
  4238.1    0.07       0  4986.5    0.07       0  4991.4    0.07       0
Bank Sta=4986.5,4991.4
Exp/Cntr=0.3,0.1

Type RM Length L Ch R = 1,14621,787,787,787
BEGIN DESCRIPTION:
Bitter Creek Trib1T2 23.1
END DESCRIPTION:
XS GIS Cut Line= 3
      1418903.78      6783597.34      1418928.64      6782914.79
      1417769.03      6781519.19
#Sta/Elev= 30
  4317.0 2507.69  4446.4 2505.15  4506.5 2506.21  4576.5 2504.04  4786.7 2503.45
  4826.7 2501.49  5026.3 2500.64  5026.7 2500.14  5031.2 2500.64  5213.6 2500.90
  5220.2 2502.13  5228.0 2501.33  5234.5 2502.89  5263.1 2501.72  5283.9 2503.03
  5291.8 2501.79  5326.9 2503.29  5341.2 2501.41  5347.7 2502.25  5355.6 2501.47
  5362.1 2502.74  5369.9 2502.03  5376.4 2503.19  5419.4 2502.12  5873.8 2503.54
  5951.9 2503.93  5987.1 2505.33  6675.8 2505.73  6725.3 2507.48  6814.5 2508.32
#Mann=3,-1,0
  4317.0    0.07       0  5026.3    0.07       0  5031.2    0.07       0
Bank Sta=5026.3,5031.2
Exp/Cntr=0.3,0.1

Type RM Length L Ch R = 1,13834,1651,1651,1651
BEGIN DESCRIPTION:
Bitter Creek Trib1T2 23.0
END DESCRIPTION:
XS GIS Cut Line= 3
      1419218.39      6783235.35      1419238.29      6782304.57
      1418627.58      6780981.73
#Sta/Elev= 30
  4069.0 2507.61  4246.4 2504.72  4356.4 2503.92  4446.4 2504.37  4496.5 2500.44
  4566.5 2499.13  5000.0 2498.09  5004.7 2497.58  5005.1 2497.08  5009.7 2497.58
  5039.2 2498.41  5084.3 2497.74  5106.4 2499.02  5128.4 2498.13  5194.5 2498.07
  5233.8 2499.60  5256.7 2499.12  5382.4 2500.57  5422.8 2502.17  5474.2 2501.85
  5624.0 2502.94  5926.6 2502.77  5965.5 2504.28  5995.5 2503.68  6167.1 2505.11
  6273.9 2505.03  6304.7 2506.71  6327.7 2506.08  6355.3 2506.41  6457.0 2507.31
#Mann=4,-1,0
  4069.0    0.07       0  5004.7    0.07       0  5009.7    0.07       0
  6355.3   0.035       0
Bank Sta=5004.7,5009.7
Exp/Cntr=0.3,0.1

Type RM Length L Ch R = 1,12183,487,487,487
BEGIN DESCRIPTION:
Bitter Creek Trib1T2 22.0
END DESCRIPTION:
XS GIS Cut Line= 3
      1419315.60      6782943.48      1420388.26      6781970.65
      1419604.99      6779987.96
#Sta/Elev= 30
  3551.9 2504.65  3647.1 2505.12  3866.8 2503.30  4277.7 2501.85  4426.3 2500.39
  4553.4 2496.89  4589.2 2496.83  4603.4 2497.75  4833.3 2496.41  4833.8 2495.91
  4839.9 2496.41  6001.9 2498.04  6078.1 2498.03  6089.1 2498.49  6108.0 2501.30
  6121.1 2501.86  6143.2 2501.73  6174.8 2499.01  6274.6 2499.91  6324.4 2499.75
  6354.2 2501.16  6701.7 2501.10  6732.8 2503.02  6762.6 2502.01  6876.1 2502.79
  6906.0 2504.56  6924.9 2503.86  7078.0 2505.03  7110.3 2506.48  7131.8 2506.30
#Mann=5,-1,0
  3551.9    0.07       0  4833.3    0.07       0  4839.9    0.07       0
  6001.9   0.035       0  6274.6    0.07       0
Bank Sta=4833.3,4839.9
Exp/Cntr=0.3,0.1

Type RM Length L Ch R = 1,11696,499,499,499
BEGIN DESCRIPTION:
Bitter Creek Trib1T2 21.0
END DESCRIPTION:
XS GIS Cut Line= 3
      1419454.98      6783188.02      1420548.60      6782285.71
      1421955.01      6780487.99
#Sta/Elev= 30
  3582.2 2507.77  3951.6 2502.80  3980.3 2501.45  4264.3 2498.97  4455.8 2498.55
  4633.0 2496.49  4904.0 2496.53  4939.2 2493.48  4999.5 2492.54  5000.0 2492.04
  5006.2 2492.54  5038.1 2493.55  5046.2 2495.24  5052.6 2494.76  5060.6 2496.27
  5137.6 2497.60  5174.6 2496.54  5429.7 2497.30  5516.5 2498.03  5543.6 2499.49
  5814.9 2502.03  6638.7 2502.76  6761.9 2502.93  6805.0 2504.95  6834.0 2503.16
  7012.1 2504.09  7061.8 2504.84  7068.2 2505.75  7132.4 2504.79  7282.5 2505.88
#Mann=4,-1,0
  3582.2    0.07       0  4999.5    0.07       0  5006.2    0.07       0
  6638.7   0.035       0
Bank Sta=4999.5,5006.2
Exp/Cntr=0.3,0.1

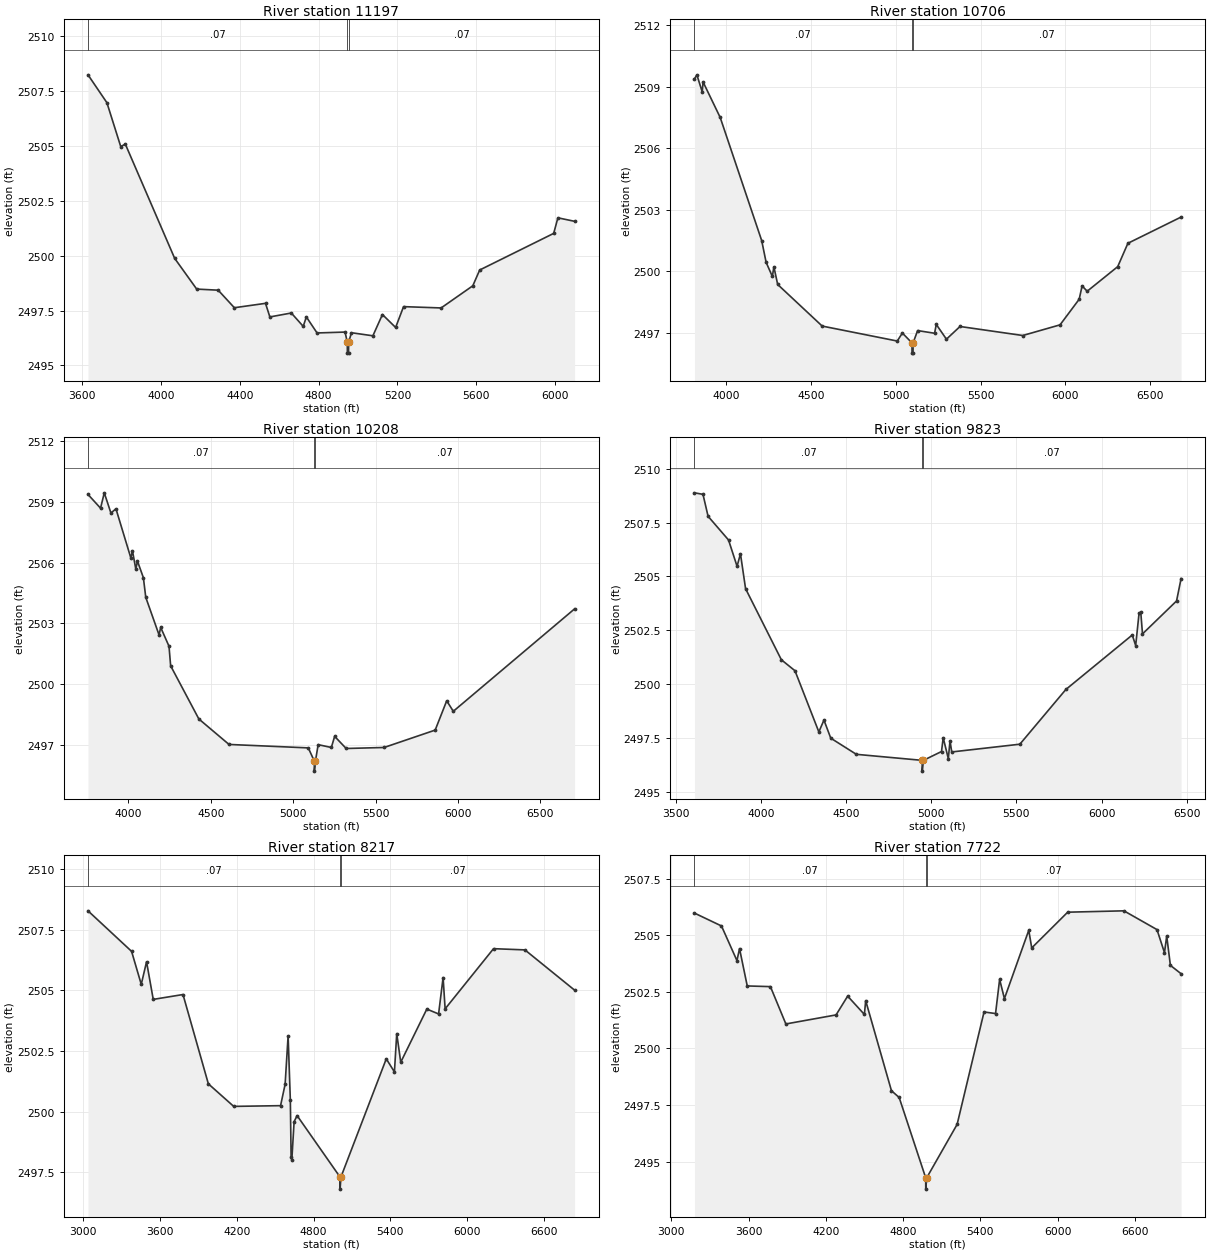
Type RM Length L Ch R = 1,11197,491,491,491
BEGIN DESCRIPTION:
Bitter Creek Trib1T2 20.0
END DESCRIPTION:
XS GIS Cut Line= 3
      1419449.50      6783250.22      1420705.49      6782701.80
      1421767.65      6782420.04
#Sta/Elev= 30
  3629.5 2508.25  3725.4 2506.98  3795.6 2504.98  3819.0 2505.09  4069.4 2499.88
  4181.1 2498.48  4290.2 2498.43  4372.2 2497.63  4530.3 2497.83  4552.4 2497.21
  4661.2 2497.39  4721.7 2496.78  4737.6 2497.21  4791.9 2496.48  4934.0 2496.52
  4945.3 2496.06  4945.8 2495.56  4951.6 2495.56  4952.1 2496.06  4966.6 2496.49
  5075.2 2496.35  5123.6 2497.32  5190.6 2496.73  5230.8 2497.68  5421.4 2497.62
  5582.2 2498.63  5617.2 2499.35  5992.7 2501.02  6014.0 2501.73  6098.9 2501.57
#Mann=3,-1,0
  3629.5    0.07       0  4945.3    0.07       0  4952.1    0.07       0
Bank Sta=4945.3,4952.1
Exp/Cntr=0.3,0.1

Type RM Length L Ch R = 1,10706,498,498,498
BEGIN DESCRIPTION:
Bitter Creek Trib1T2 19.0
END DESCRIPTION:
XS GIS Cut Line= 3
      1419431.17      6783459.13      1420556.66      6783078.22
      1422238.68      6783132.45
#Sta/Elev= 30
  3811.8 2509.39  3826.0 2509.59  3857.5 2508.76  3862.7 2509.24  3963.6 2507.51
  4208.5 2501.50  4234.6 2500.44  4271.4 2499.75  4280.4 2500.22  4302.8 2499.36
  4565.4 2497.33  5008.3 2496.60  5038.4 2496.99  5095.0 2496.51  5095.5 2496.01
  5101.3 2496.01  5101.8 2496.51  5128.4 2497.11  5228.5 2496.98  5238.5 2497.41
  5298.5 2496.69  5378.5 2497.31  5748.7 2496.87  5968.8 2497.39  6081.7 2498.64
  6098.9 2499.29  6128.9 2499.03  6309.0 2500.23  6369.1 2501.37  6682.9 2502.65
#Mann=3,-1,0
  3811.8    0.07       0  5095.0    0.07       0  5101.8    0.07       0
Bank Sta=5095,5101.8
Exp/Cntr=0.3,0.1

Type RM Length L Ch R = 1,10208,385,385,385
BEGIN DESCRIPTION:
Bitter Creek Trib1T2 18.0
END DESCRIPTION:
XS GIS Cut Line= 3
      1419416.86      6783622.17      1420653.21      6783477.36
      1422361.11      6783476.68
#Sta/Elev= 30
  3755.2 2509.38  3831.4 2508.70  3854.0 2509.46  3894.3 2508.46  3924.8 2508.67
  4015.1 2506.24  4025.2 2506.58  4045.3 2505.69  4055.4 2506.08  4091.3 2505.26
  4105.7 2504.29  4186.3 2502.43  4196.3 2502.80  4246.7 2501.87  4256.7 2500.90
  4427.9 2498.27  4610.9 2497.01  5091.8 2496.84  5128.3 2496.19  5128.8 2495.69
  5135.3 2496.19  5151.8 2497.00  5231.8 2496.86  5251.8 2497.41  5321.8 2496.81
  5551.8 2496.86  5861.8 2497.72  5931.8 2499.17  5971.8 2498.65  6707.9 2503.72
#Mann=3,-1,0
  3755.2    0.07       0  5128.3    0.07       0  5135.3    0.07       0
Bank Sta=5128.3,5135.3
Exp/Cntr=0.3,0.1

Type RM Length L Ch R = 1,9823,1606,1606,1606
BEGIN DESCRIPTION:
Bitter Creek Trib1T2 17.0
END DESCRIPTION:
XS GIS Cut Line= 3
      1419455.02      6783688.00      1420844.65      6783727.88
      1422311.63      6783719.93
#Sta/Elev= 30
  3609.8 2508.88  3659.8 2508.81  3689.8 2507.79  3809.9 2506.69  3859.9 2505.47
  3879.9 2506.05  3909.9 2504.43  4120.0 2501.13  4200.0 2500.62  4340.1 2497.78
  4370.1 2498.33  4410.1 2497.49  4560.2 2496.74  4946.8 2496.46  4947.3 2495.96
  4953.9 2496.46  5060.3 2496.87  5070.3 2497.51  5100.3 2496.54  5110.3 2497.37
  5120.3 2496.85  5520.4 2497.21  5790.4 2499.75  6180.4 2502.28  6200.4 2501.79
  6220.4 2503.30  6230.4 2503.33  6240.4 2502.33  6440.4 2503.86  6467.0 2504.90
#Mann=3,-1,0
  3609.8    0.07       0  4946.8    0.07       0  4953.9    0.07       0
Bank Sta=4946.8,4953.9
Exp/Cntr=0.3,0.1

Type RM Length L Ch R = 1,8217,495,495,495
BEGIN DESCRIPTION:
Bitter Creek Trib1T2 16.0
END DESCRIPTION:
XS GIS Cut Line= 3
      1419504.98      6783937.99      1421304.59      6784722.81
      1423105.02      6784337.99
#Sta/Elev= 30
  3036.7 2508.28  3377.4 2506.61  3453.1 2505.25  3494.5 2506.18  3546.8 2504.63
  3779.4 2504.83  3977.6 2501.15  4175.9 2500.22  4542.2 2500.25  4577.8 2501.13
  4601.2 2503.13  4618.6 2500.48  4624.6 2498.14  4630.1 2498.01  4648.1 2499.59
  4671.5 2499.84  5007.0 2497.31  5007.5 2496.81  5014.3 2497.31  5368.6 2502.18
  5432.4 2501.64  5450.4 2503.22  5481.8 2502.04  5685.6 2504.23  5777.6 2504.03
  5812.9 2505.53  5828.7 2504.24  6207.1 2506.72  6452.5 2506.67  6841.1 2505.01
#Mann=3,-1,0
  3036.7    0.07       0  5007.0    0.07       0  5014.3    0.07       0
Bank Sta=5007,5014.3
Exp/Cntr=0.3,0.1

Type RM Length L Ch R = 1,7722,491,491,491
BEGIN DESCRIPTION:
Bitter Creek Trib1T2 15.0
END DESCRIPTION:
XS GIS Cut Line= 3
      1419655.03      6785138.00      1421475.82      6785158.03
      1423255.03      6784337.98
#Sta/Elev= 30
  3179.1 2505.98  3389.1 2505.41  3509.1 2503.88  3529.1 2504.41  3589.1 2502.76
  3769.1 2502.73  3889.1 2501.08  4279.1 2501.48  4369.1 2502.31  4499.1 2501.50
  4509.1 2502.11  4709.2 2498.13  4769.2 2497.83  4975.3 2494.28  4975.8 2493.78
  4983.0 2494.28  5219.3 2496.64  5428.5 2501.61  5517.9 2501.54  5549.6 2503.05
  5586.8 2502.20  5775.9 2505.22  5798.9 2504.44  6078.2 2506.02  6515.1 2506.08
  6771.9 2505.25  6830.1 2504.23  6847.5 2504.97  6876.0 2503.67  6959.1 2503.30
#Mann=3,-1,0
  3179.1    0.07       0  4975.3    0.07       0  4983.0    0.07       0
Bank Sta=4975.3,4983
Exp/Cntr=0.3,0.1

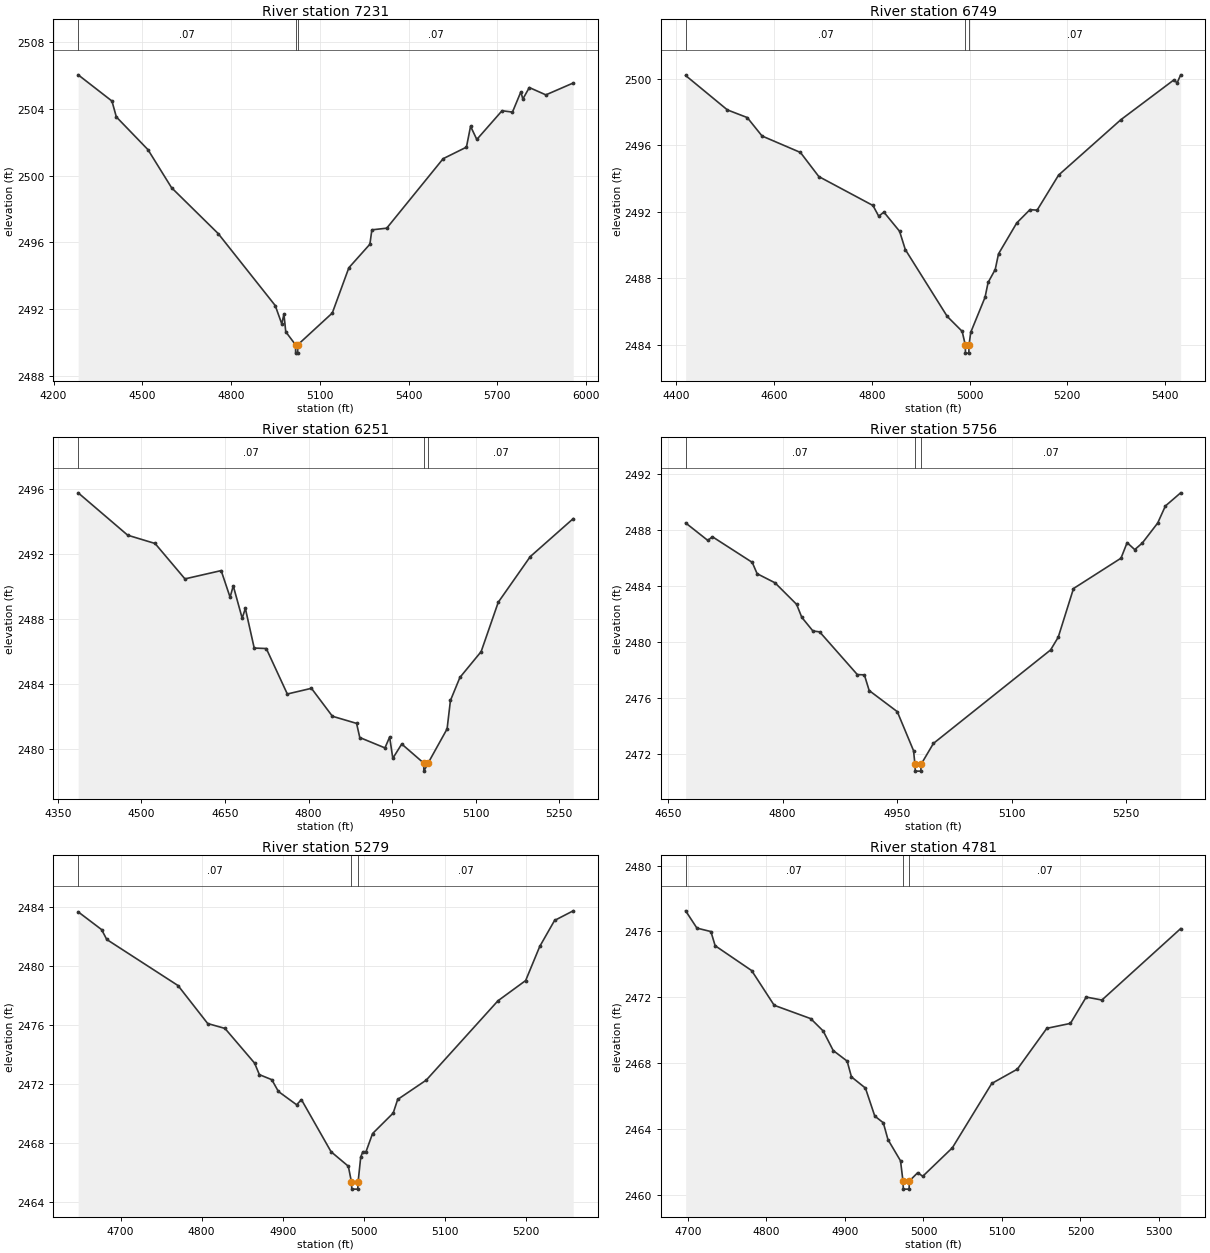
Type RM Length L Ch R = 1,7231,482,482,482
BEGIN DESCRIPTION:
Bitter Creek Trib1T2 14.0
END DESCRIPTION:
XS GIS Cut Line= 3
      1421155.03      6785887.98      1421738.42      6785471.16
      1422454.98      6784838.02
#Sta/Elev= 30
  4283.0 2506.03  4397.2 2504.46  4412.0 2503.51  4518.9 2501.55  4598.8 2499.27
  4756.1 2496.53  4949.0 2492.22  4971.2 2491.12  4978.5 2491.71  4984.6 2490.65
  5017.6 2489.87  5018.1 2489.37  5024.8 2489.37  5025.3 2489.87  5141.9 2491.77
  5197.9 2494.48  5269.0 2495.89  5275.7 2496.75  5325.9 2496.85  5516.6 2501.01
  5595.3 2501.70  5609.3 2502.95  5630.4 2502.16  5715.7 2503.88  5750.9 2503.80
  5779.3 2505.01  5786.0 2504.58  5807.8 2505.27  5863.8 2504.83  5956.2 2505.54
#Mann=3,-1,0
  4283.0    0.07       0  5017.6    0.07       0  5025.3    0.07       0
Bank Sta=5017.6,5025.3
Exp/Cntr=0.3,0.1

Type RM Length L Ch R = 1,6749,498,498,498
BEGIN DESCRIPTION:
Bitter Creek Trib1T2 13.0
END DESCRIPTION:
XS GIS Cut Line= 3
      1421504.96      6785988.02      1422049.17      6785785.70
      1422305.01      6785437.98
#Sta/Elev= 30
  4419.4 2500.20  4504.8 2498.13  4545.4 2497.67  4575.7 2496.56  4654.2 2495.57
  4691.8 2494.12  4802.5 2492.38  4814.2 2491.74  4824.9 2491.98  4856.9 2490.83
  4868.6 2489.73  4954.3 2485.71  4984.9 2484.81  4991.2 2484.00  4991.7 2483.50
  4998.5 2483.50  4999.0 2484.00  5002.4 2484.75  5031.7 2486.86  5037.9 2487.75
  5052.5 2488.53  5059.2 2489.47  5096.5 2491.33  5123.5 2492.13  5138.2 2492.10
  5182.1 2494.21  5309.4 2497.54  5418.1 2499.94  5424.4 2499.75  5431.7 2500.24
#Mann=3,-1,0
  4419.4    0.07       0  4991.2    0.07       0  4999.0    0.07       0
Bank Sta=4991.2,4999
Exp/Cntr=0.3,0.1

Type RM Length L Ch R = 1,6251,495,495,495
BEGIN DESCRIPTION:
Bitter Creek Trib1T2 12.0
END DESCRIPTION:
XS GIS Cut Line= 3
      1421755.01      6786388.00      1422289.81      6786087.59
      1422405.00      6785837.99
#Sta/Elev= 30
  4386.6 2495.79  4475.5 2493.18  4524.6 2492.67  4578.2 2490.49  4643.2 2491.00
  4659.2 2489.36  4664.9 2490.06  4680.9 2488.07  4686.6 2488.67  4702.5 2486.23
  4724.2 2486.20  4761.9 2483.40  4805.2 2483.75  4842.8 2482.03  4886.2 2481.59
  4891.9 2480.72  4937.1 2480.08  4945.5 2480.75  4951.2 2479.44  4967.2 2480.32
  5006.5 2479.15  5007.0 2478.65  5014.6 2479.15  5048.6 2481.25  5054.6 2483.00
  5071.6 2484.42  5109.7 2486.01  5140.4 2489.05  5197.8 2491.86  5274.9 2494.20
#Mann=3,-1,0
  4386.6    0.07       0  5006.5    0.07       0  5014.6    0.07       0
Bank Sta=5006.5,5014.6
Exp/Cntr=0.3,0.1

Type RM Length L Ch R = 1,5756,477,477,477
BEGIN DESCRIPTION:
Bitter Creek Trib1T2 11.0
END DESCRIPTION:
XS GIS Cut Line= 3
      1422505.02      6786637.97      1422674.80      6786358.49
      1422655.00      6786038.00
#Sta/Elev= 30
  4673.0 2488.49  4702.0 2487.24  4708.1 2487.50  4760.2 2485.67  4766.6 2484.86
  4790.0 2484.21  4818.3 2482.67  4825.1 2481.74  4839.6 2480.77  4848.5 2480.70
  4897.8 2477.65  4907.0 2477.63  4913.3 2476.51  4950.1 2475.00  4971.4 2472.21
  4973.2 2471.25  4973.7 2470.75  4980.9 2470.75  4981.4 2471.25  4997.4 2472.73
  5150.8 2479.41  5160.8 2480.32  5180.8 2483.80  5243.0 2485.97  5251.0 2487.08
  5261.0 2486.58  5271.0 2487.06  5291.0 2488.48  5301.1 2489.70  5321.1 2490.64
#Mann=3,-1,0
  4673.0    0.07       0  4973.2    0.07       0  4981.4    0.07       0
Bank Sta=4973.2,4981.4
Exp/Cntr=0.3,0.1

Type RM Length L Ch R = 1,5279,498,498,498
BEGIN DESCRIPTION:
Bitter Creek Trib1T2 10.0
END DESCRIPTION:
XS GIS Cut Line= 3
      1422955.02      6786687.96      1423141.08      6786388.68
      1423205.00      6786138.00
#Sta/Elev= 30
  4647.6 2483.65  4676.5 2482.45  4682.9 2481.78  4770.9 2478.66  4807.5 2476.09
  4828.8 2475.76  4865.4 2473.41  4871.3 2472.63  4886.6 2472.29  4894.8 2471.49
  4917.3 2470.59  4923.2 2470.94  4959.8 2467.41  4981.1 2466.43  4984.9 2465.38
  4985.4 2464.88  4992.7 2464.88  4993.2 2465.38  4996.4 2467.05  4999.0 2467.41
  5002.9 2467.41  5011.0 2468.64  5036.5 2470.03  5042.0 2470.95  5077.3 2472.26
  5165.8 2477.63  5200.0 2479.00  5217.4 2481.31  5235.7 2483.07  5258.7 2483.72
#Mann=3,-1,0
  4647.6    0.07       0  4984.9    0.07       0  4993.2    0.07       0
Bank Sta=4984.9,4993.2
Exp/Cntr=0.3,0.1

Type RM Length L Ch R = 1,4781,397,397,397
BEGIN DESCRIPTION:
Bitter Creek Trib1T2 9.0
END DESCRIPTION:
XS GIS Cut Line= 3
      1423254.96      6786788.02      1423531.64      6786664.74
      1423555.00      6786337.97
#Sta/Elev= 30
  4697.1 2477.25  4711.5 2476.20  4729.3 2475.99  4734.7 2475.13  4781.2 2473.62
  4809.9 2471.51  4856.4 2470.70  4872.3 2469.95  4885.1 2468.76  4902.8 2468.12
  4908.3 2467.16  4926.1 2466.48  4938.0 2464.78  4948.9 2464.37  4954.8 2463.35
  4970.8 2462.06  4973.9 2460.84  4974.4 2460.34  4981.7 2460.34  4982.2 2460.84
  4992.7 2461.34  4999.1 2461.12  5036.8 2462.85  5087.0 2466.76  5119.6 2467.63
  5157.1 2470.11  5187.2 2470.41  5207.3 2472.01  5227.3 2471.83  5327.6 2476.17
#Mann=3,-1,0
  4697.1    0.07       0  4973.9    0.07       0  4982.2    0.07       0
Bank Sta=4973.9,4982.2
Exp/Cntr=0.3,0.1