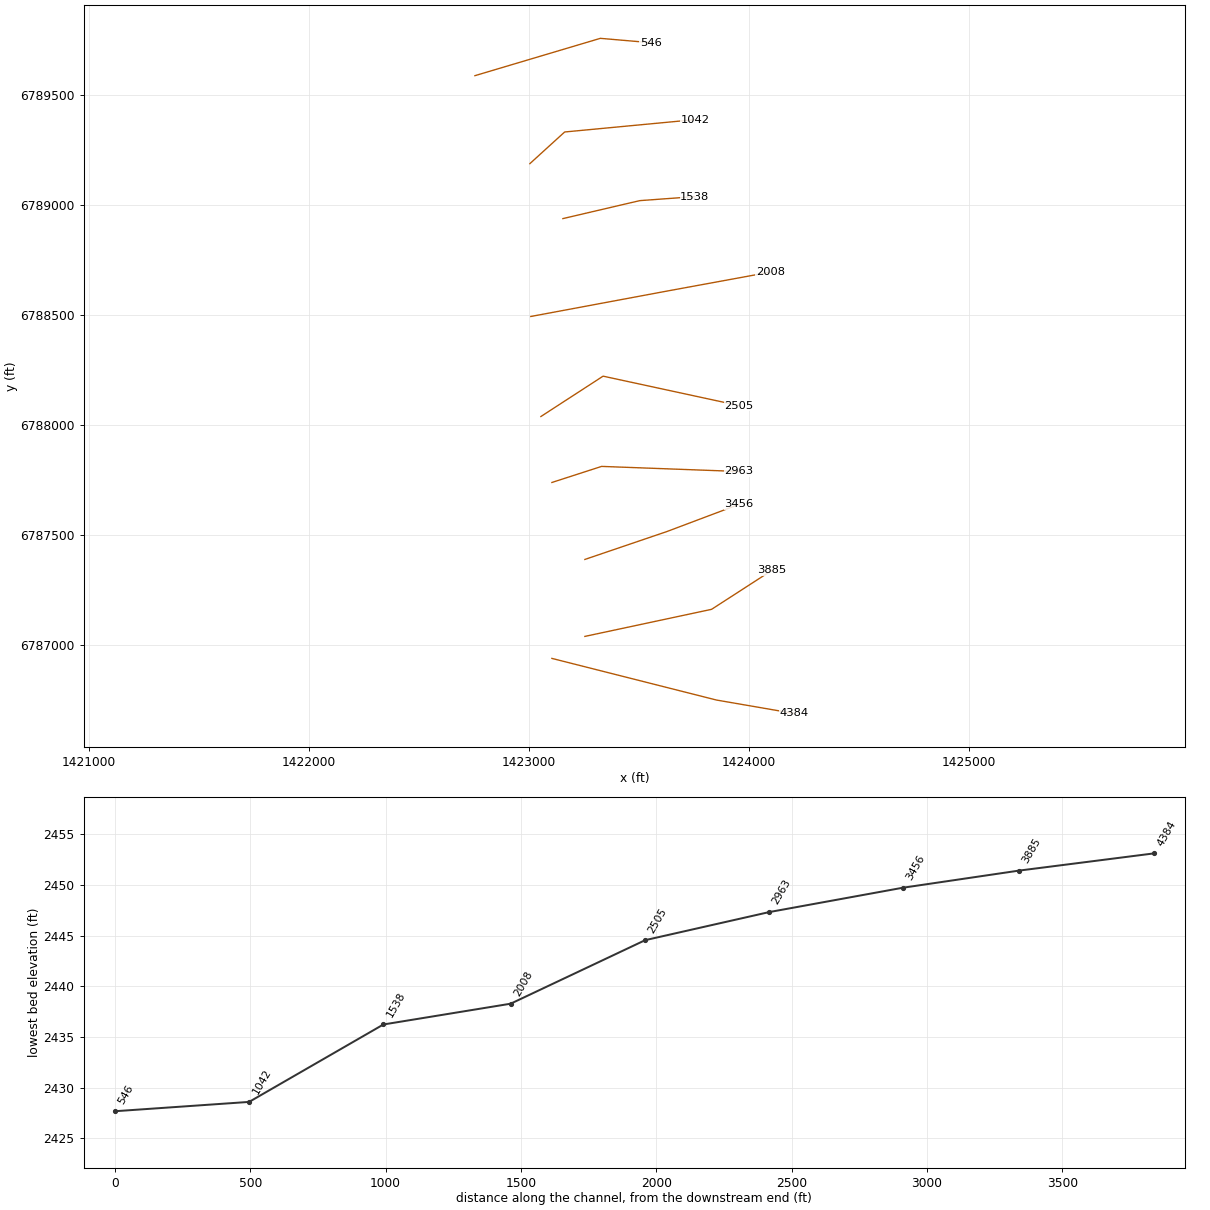
HEC-RAS study Bitter Creek Trib1T2.prj: Bitter Creek Trib1T2 Base Level Engineering

--- Bitter Creek Trib1T2.g01 (geometry) --- (continued)

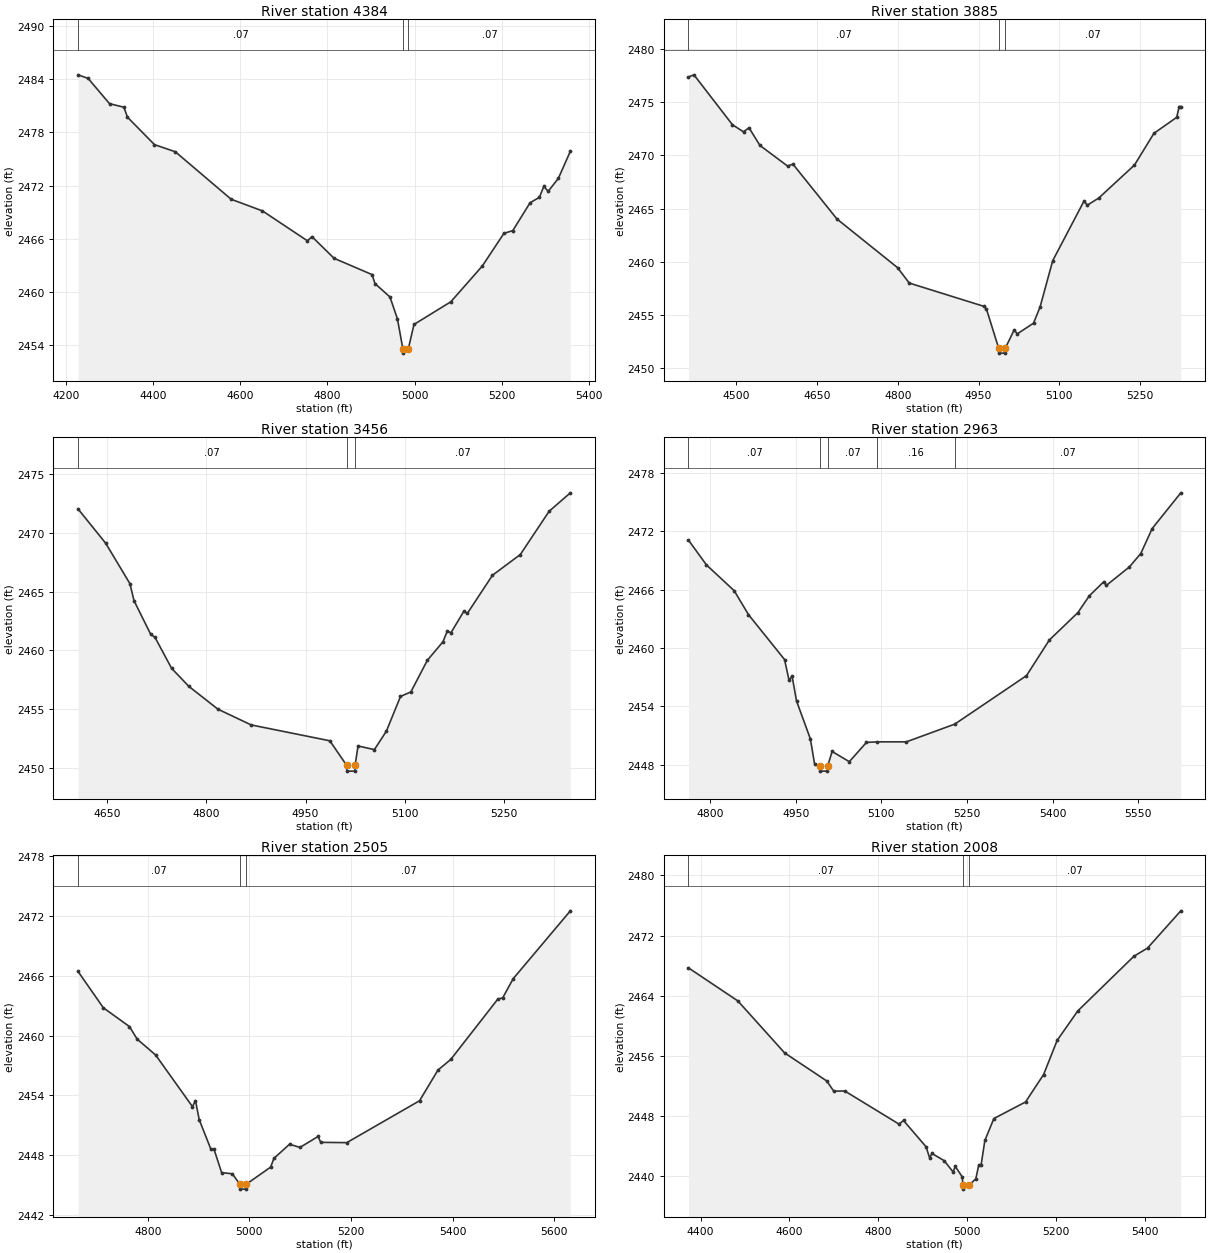
Type RM Length L Ch R = 1,4384,499,499,499
BEGIN DESCRIPTION:
Bitter Creek Trib1T2 8.0
END DESCRIPTION:
XS GIS Cut Line= 3
      1423105.02      6786937.99      1423853.35      6786748.68
      1424205.05      6786687.99
#Sta/Elev= 30
  4228.1 2484.50  4251.2 2484.10  4300.3 2481.25  4333.2 2480.85  4341.5 2479.72
  4403.4 2476.63  4451.1 2475.83  4579.3 2470.47  4651.0 2469.16  4754.1 2465.79
  4764.5 2466.26  4815.1 2463.82  4902.3 2461.98  4908.9 2460.97  4943.3 2459.46
  4960.4 2456.99  4972.8 2453.63  4973.3 2453.13  4985.5 2453.63  4998.3 2456.36
  5082.9 2458.92  5155.0 2462.95  5204.6 2466.63  5224.9 2466.94  5264.5 2470.08
  5285.8 2470.69  5296.0 2471.92  5306.1 2471.37  5329.5 2472.84  5356.9 2475.89
#Mann=3,-1,0
  4228.1    0.07       0  4972.8    0.07       0  4985.5    0.07       0
Bank Sta=4972.8,4985.5
Exp/Cntr=0.3,0.1

Type RM Length L Ch R = 1,3885,429,429,429
BEGIN DESCRIPTION:
Bitter Creek Trib1T2 7.0
END DESCRIPTION:
XS GIS Cut Line= 3
      1423254.99      6787038.00      1423831.18      6787161.13
      1424105.02      6787338.01
#Sta/Elev= 30
  4410.8 2477.36  4421.0 2477.56  4492.6 2472.87  4513.1 2472.21  4523.3 2472.59
  4543.7 2470.93  4594.9 2469.00  4605.1 2469.17  4686.9 2464.02  4799.4 2459.46
  4821.2 2458.01  4959.5 2455.83  4964.6 2455.59  4987.2 2451.93  4987.7 2451.43
  4999.6 2451.43  5000.1 2451.93  5016.2 2453.60  5022.1 2453.24  5052.2 2454.24
  5064.4 2455.76  5087.9 2460.11  5146.2 2465.72  5152.1 2465.32  5173.2 2465.98
  5239.9 2469.09  5276.1 2472.07  5318.4 2473.57  5323.0 2474.58  5326.0 2474.58
#Mann=3,-1,0
  4410.8    0.07       0  4987.2    0.07       0  5000.1    0.07       0
Bank Sta=4987.2,5000.1
Exp/Cntr=0.3,0.1

Type RM Length L Ch R = 1,3456,493,493,493
BEGIN DESCRIPTION:
Bitter Creek Trib1T2 6.0
END DESCRIPTION:
XS GIS Cut Line= 3
      1423255.02      6787388.01      1423627.57      6787514.69
      1423955.02      6787638.01
#Sta/Elev= 30
  4606.5 2472.04  4648.3 2469.12  4684.9 2465.68  4691.0 2464.24  4716.3 2461.37
  4722.7 2461.12  4747.7 2458.49  4773.8 2456.95  4817.7 2455.01  4867.9 2453.67
  4986.7 2452.32  5012.0 2450.24  5012.5 2449.74  5024.4 2449.74  5024.9 2450.24
  5029.3 2451.88  5054.0 2451.57  5072.1 2453.14  5093.4 2456.09  5109.1 2456.48
  5134.0 2459.17  5157.5 2460.74  5164.2 2461.67  5169.5 2461.50  5189.0 2463.33
  5194.4 2463.16  5232.3 2466.40  5274.3 2468.16  5317.8 2471.84  5349.9 2473.41
#Mann=3,-1,0
  4606.5    0.07       0  5012.0    0.07       0  5024.9    0.07       0
Bank Sta=5012,5024.9
Exp/Cntr=0.3,0.1

Type RM Length L Ch R = 1,2963,458,458,458
BEGIN DESCRIPTION:
Bitter Creek Trib1T2 5.0
END DESCRIPTION:
XS GIS Cut Line= 3
      1423104.99      6787738.00      1423331.16      6787811.12
      1423955.04      6787788.00
#Sta/Elev= 30
  4762.3 2471.08  4793.8 2468.53  4842.4 2465.88  4867.4 2463.42  4930.5 2458.81
  4938.4 2456.67  4943.7 2457.11  4951.5 2454.55  4975.7 2450.66  4983.0 2448.12
  4992.9 2447.84  4993.4 2447.34  5005.4 2447.34  5005.9 2447.84  5013.8 2449.36
  5043.9 2448.31  5073.9 2450.29  5093.1 2450.35  5143.9 2450.35  5228.5 2452.17
  5354.1 2457.15  5394.1 2460.81  5444.1 2463.63  5464.2 2465.36  5489.2 2466.79
  5494.2 2466.44  5534.2 2468.32  5554.2 2469.70  5574.2 2472.27  5624.3 2475.94
#Mann=5,-1,0
  4762.3    0.07       0  4992.9    0.07       0  5005.9    0.07       0
  5093.1    0.16       0  5228.5    0.07       0
Bank Sta=4992.9,5005.9
Exp/Cntr=0.3,0.1

Type RM Length L Ch R = 1,2505,497,497,497
BEGIN DESCRIPTION:
Bitter Creek Trib1T2 4.0
END DESCRIPTION:
XS GIS Cut Line= 3
      1423054.99      6788037.99      1423337.88      6788221.52
      1423955.00      6788088.00
#Sta/Elev= 30
  4662.8 2466.44  4712.6 2462.79  4764.0 2460.90  4779.1 2459.64  4815.4 2458.05
  4887.9 2452.86  4893.9 2453.46  4901.2 2451.55  4924.2 2448.58  4930.1 2448.61
  4945.3 2446.23  4966.4 2446.11  4981.0 2445.07  4981.5 2444.57  4993.5 2444.57
  4994.0 2445.07  5041.7 2446.78  5048.2 2447.66  5078.9 2449.08  5099.4 2448.76
  5135.0 2449.86  5140.3 2449.27  5191.5 2449.24  5334.7 2453.45  5370.9 2456.53
  5396.1 2457.60  5488.2 2463.63  5498.4 2463.80  5518.9 2465.71  5631.4 2472.53
#Mann=3,-1,0
  4662.8    0.07       0  4981.0    0.07       0  4994.0    0.07       0
Bank Sta=4981,4994
Exp/Cntr=0.3,0.1

Type RM Length L Ch R = 1,2008,470,470,470
BEGIN DESCRIPTION:
Bitter Creek Trib1T2 3.0
END DESCRIPTION:
XS GIS Cut Line= 3
      1423009.28      6788492.91      1423625.94      6788607.98
      1424098.64      6788694.73
#Sta/Elev= 30
  4372.7 2467.70  4483.8 2463.31  4589.1 2456.40  4683.7 2452.68  4699.6 2451.32
  4724.4 2451.34  4846.5 2446.94  4856.6 2447.42  4907.5 2443.92  4915.4 2442.44
  4920.5 2443.04  4948.2 2442.08  4968.1 2440.59  4973.2 2441.31  4988.9 2439.92
  4990.4 2438.80  4990.9 2438.30  5003.6 2438.80  5019.4 2439.68  5026.1 2441.55
  5031.2 2441.50  5039.7 2444.77  5060.0 2447.68  5131.2 2449.88  5171.9 2453.53
  5202.4 2458.07  5248.8 2461.98  5375.2 2469.25  5405.7 2470.33  5480.6 2475.28
#Mann=3,-1,0
  4372.7    0.07       0  4990.4    0.07       0  5003.6    0.07       0
Bank Sta=4990.4,5003.6
Exp/Cntr=0.3,0.1

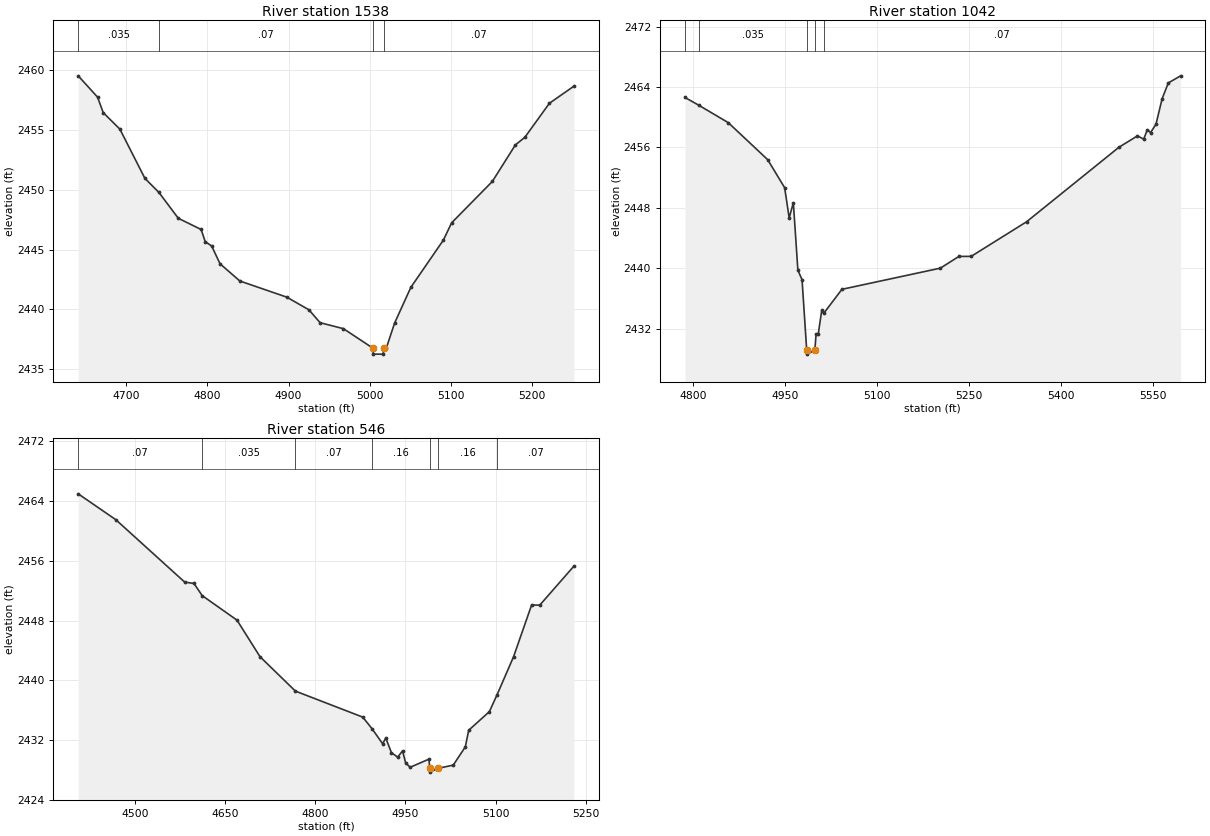
Type RM Length L Ch R = 1,1538,496,496,496
BEGIN DESCRIPTION:
Bitter Creek Trib1T2 2.0
END DESCRIPTION:
XS GIS Cut Line= 3
      1423155.02      6788938.00      1423504.50      6789019.70
      1423755.03      6789038.00
#Sta/Elev= 30
  4641.1 2459.54  4664.9 2457.76  4671.9 2456.46  4692.4 2455.08  4723.2 2450.96
  4740.5 2449.78  4764.3 2447.62  4792.4 2446.68  4797.5 2445.66  4805.4 2445.30
  4815.7 2443.81  4840.1 2442.37  4897.8 2441.02  4925.1 2439.96  4938.9 2438.88
  4967.6 2438.38  5003.9 2436.75  5004.4 2436.25  5016.6 2436.25  5017.1 2436.75
  5020.6 2436.80  5030.6 2438.85  5050.6 2441.84  5090.7 2445.80  5100.8 2447.24
  5150.9 2450.70  5179.3 2453.76  5191.0 2454.40  5221.1 2457.24  5251.2 2458.67
#Mann=4,-1,0
  4641.1   0.035       0  4740.5    0.07       0  5003.9    0.07       0
  5017.1    0.07       0
Bank Sta=5003.9,5017.1
Exp/Cntr=0.3,0.1

Type RM Length L Ch R = 1,1042,496,496,496
BEGIN DESCRIPTION:
Bitter Creek Trib1T2 1.0
END DESCRIPTION:
XS GIS Cut Line= 3
      1423004.99      6789187.99      1423163.09      6789331.92
      1423755.04      6789388.00
#Sta/Elev= 30
  4786.2 2462.63  4808.7 2461.60  4856.8 2459.29  4921.0 2454.39  4948.7 2450.67
  4956.1 2446.67  4962.9 2448.68  4970.3 2439.73  4977.1 2438.48  4984.7 2429.11
  4985.2 2428.61  4997.9 2429.11  5000.0 2431.26  5003.5 2431.26  5009.2 2434.41
  5012.3 2434.00  5042.1 2437.20  5202.8 2440.01  5232.9 2441.56  5253.0 2441.57
  5343.4 2446.16  5494.1 2456.04  5524.2 2457.54  5534.3 2457.11  5540.4 2458.36
  5545.5 2457.97  5554.4 2459.08  5564.4 2462.46  5574.5 2464.56  5594.6 2465.50
#Mann=5,-1,0
  4786.2    0.07       0  4808.7   0.035       0  4984.7   0.035       0
  4997.9   0.035       0  5012.3    0.07       0
Bank Sta=4984.7,4997.9
Exp/Cntr=0.3,0.1

Type RM Length L Ch R = 1,546,0,0,0
BEGIN DESCRIPTION:
Bitter Creek Trib1T2 0.1
END DESCRIPTION:
XS GIS Cut Line= 3
      1422755.02      6789588.01      1423325.49      6789757.80
      1423555.04      6789738.00
#Sta/Elev= 30
  4404.8 2464.97  4467.4 2461.51  4582.1 2453.15  4597.7 2452.96  4611.3 2451.34
  4669.3 2448.05  4707.7 2443.15  4766.7 2438.54  4878.8 2435.06  4894.7 2433.46
  4911.9 2431.49  4917.2 2432.25  4926.5 2430.31  4936.9 2429.69  4945.1 2430.53
  4950.3 2428.92  4957.8 2428.34  4989.1 2429.43  4990.4 2428.19  4990.9 2427.69
  5003.8 2428.19  5029.6 2428.63  5049.7 2431.08  5055.3 2433.30  5089.8 2435.80
  5102.6 2438.06  5130.0 2443.14  5160.1 2450.08  5173.7 2450.06  5230.4 2455.27
#Mann=7,-1,0
  4404.8    0.07       0  4611.3   0.035       0  4766.7    0.07       0
  4894.7    0.16       0  4990.4    0.07       0  5003.8    0.16       0
  5102.6    0.07       0
Bank Sta=4990.4,5003.8
Exp/Cntr=0.3,0.1

Chan Stop Cuts=-1