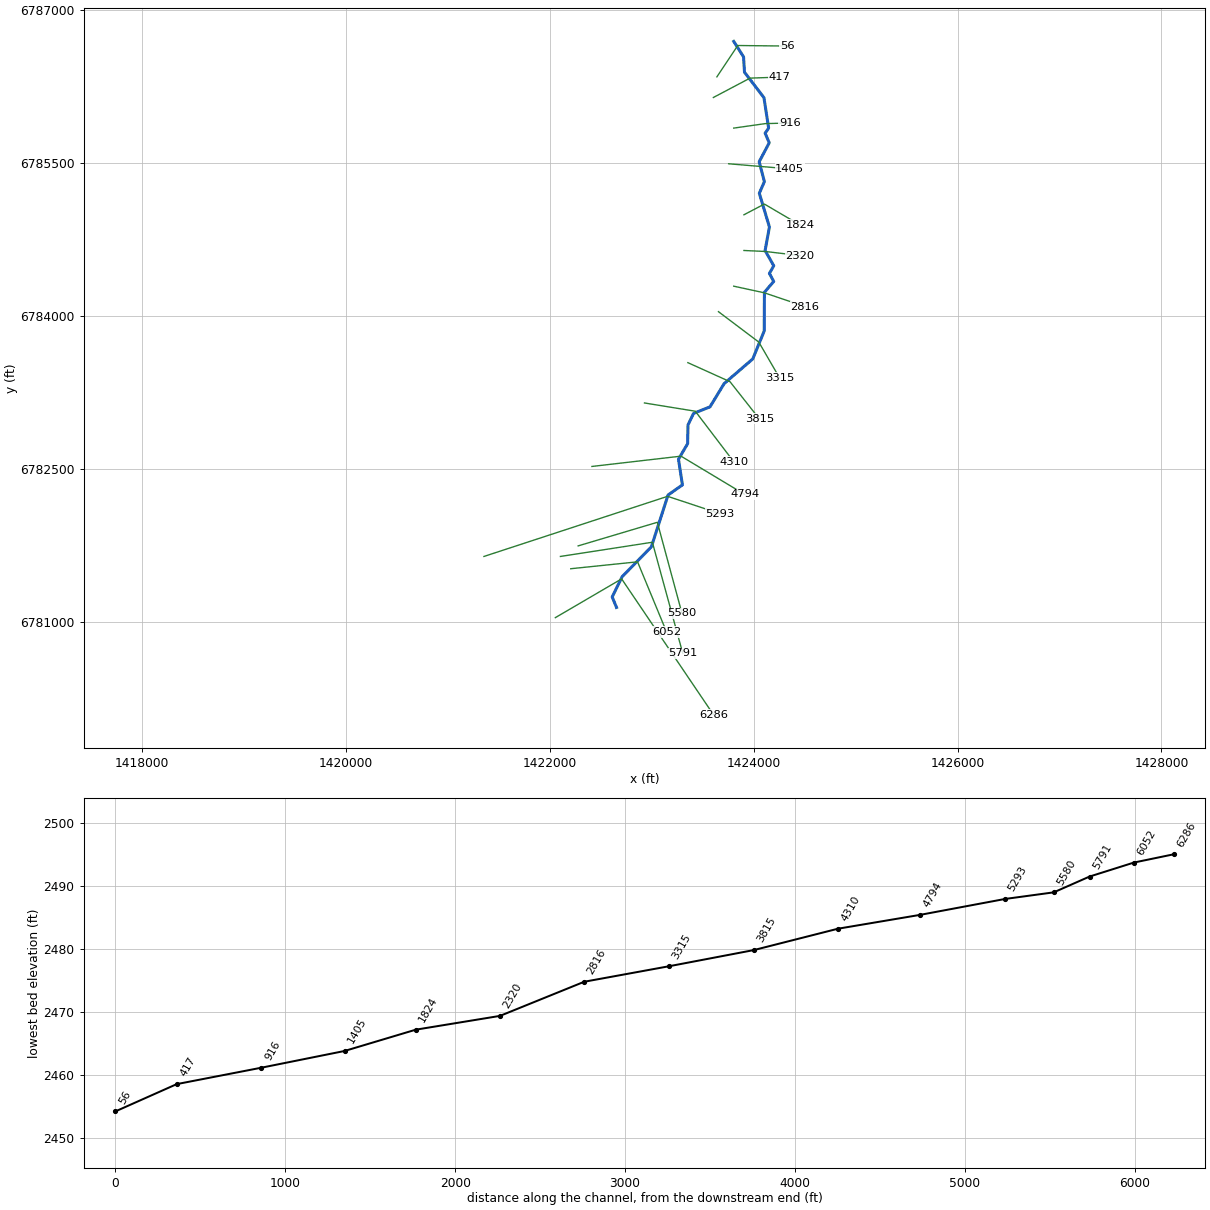
--- Bitter Creek Trib1T2_1.prj (project) ---

Proj Title=Bitter Creek Trib1T2_1 Base Level Engineering
Current Plan=p01
Default Exp/Contr=0.3,0.1
English Units
Geom File=g01
Flow File=f01
Plan File=p01
BEGIN DESCRIPTION:
Bitter Creek Trib1T2_1
END DESCRIPTION:

--- Bitter Creek Trib1T2_1.p01 (plan) ---

Plan Title=Multiple Run
Short Identifier=Multiple
Geom File=g01
Flow File=f01
Subcritical Flow
K Sum by GR= 0
Std Step Tol= 0.01
Critical Tol= 0.01
Num of Std Step Trials= 20
Max Error Tol= 0.3
Flow Tol Ratio= 0.001
Split Flow NTrial= 30
Split Flow Tol= 0.02
Split Flow Ratio= 0.02
Log Output Level= 0
Friction Slope Method= 1
Unsteady Friction Slope Method= 2
Unsteady Bridges Friction Slope Method= 1
Parabolic Critical Depth
Global Vel Dist=  1 , 1 , 1
Global Log Level= 0
CheckData=True
Encroach Param= -1, 0, 0, 0
BEGIN DESCRIPTION:
Multiple Run
END DESCRIPTION:

--- Bitter Creek Trib1T2_1.f01 (steady flow) ---

Flow Title=Multiple
Number of Profiles=7
Profile Names=10-year,25-year,50-year,1pct_min,100-year,1pct_plu,500-year
River Rch & RM= Bitter Creek Tri,Reach-1,6286
      96     120     137      78     155     310     201
River Rch & RM= Bitter Creek Tri,Reach-1,5580
     272     373     455     275     549    1096     811
Boundary for River Rch & Prof#=Bitter Creek Tri,Reach-1,1
Up Type=0
Dn Type=3
Dn Slope=0.005
Boundary for River Rch & Prof#=Bitter Creek Tri,Reach-1,2
Up Type=0
Dn Type=3
Dn Slope=0.005
Boundary for River Rch & Prof#=Bitter Creek Tri,Reach-1,3
Up Type=0
Dn Type=3
Dn Slope=0.005
Boundary for River Rch & Prof#=Bitter Creek Tri,Reach-1,4
Up Type=0
Dn Type=3
Dn Slope=0.005
Boundary for River Rch & Prof#=Bitter Creek Tri,Reach-1,5
Up Type=0
Dn Type=3
Dn Slope=0.005
Boundary for River Rch & Prof#=Bitter Creek Tri,Reach-1,6
Up Type=0
Dn Type=3
Dn Slope=0.005
Boundary for River Rch & Prof#=Bitter Creek Tri,Reach-1,7
Up Type=0
Dn Type=3
Dn Slope=0.005

--- Bitter Creek Trib1T2_1.g01 (geometry) ---

Geom Title=Existing Conditions

River Reach=Bitter Creek Tri,Reach-1
Reach XY= 30
      1422655.00      6781138.00      1422612.85      6781241.28
      1422710.83      6781440.30      1422996.84      6781731.95
      1423160.73      6782240.55      1423301.55      6782339.25
      1423263.04      6782591.32      1423352.76      6782743.93
      1423356.20      6782927.50      1423410.71      6783040.58
      1423571.79      6783104.44      1423710.59      6783332.39
      1423991.60      6783574.70      1424103.80      6783848.50
      1424106.06      6784227.57      1424197.17      6784334.60
      1424154.78      6784413.00      1424197.44      6784488.00
      1424112.53      6784637.99      1424154.93      6784867.97
      1424055.77      6785198.69      1424105.39      6785313.00
      1424054.60      6785508.14      1424153.16      6785694.13
      1424112.83      6785788.08      1424147.21      6785837.90
      1424101.25      6786136.45      1423910.47      6786385.55
      1423901.25      6786536.45      1423805.00      6786688.00

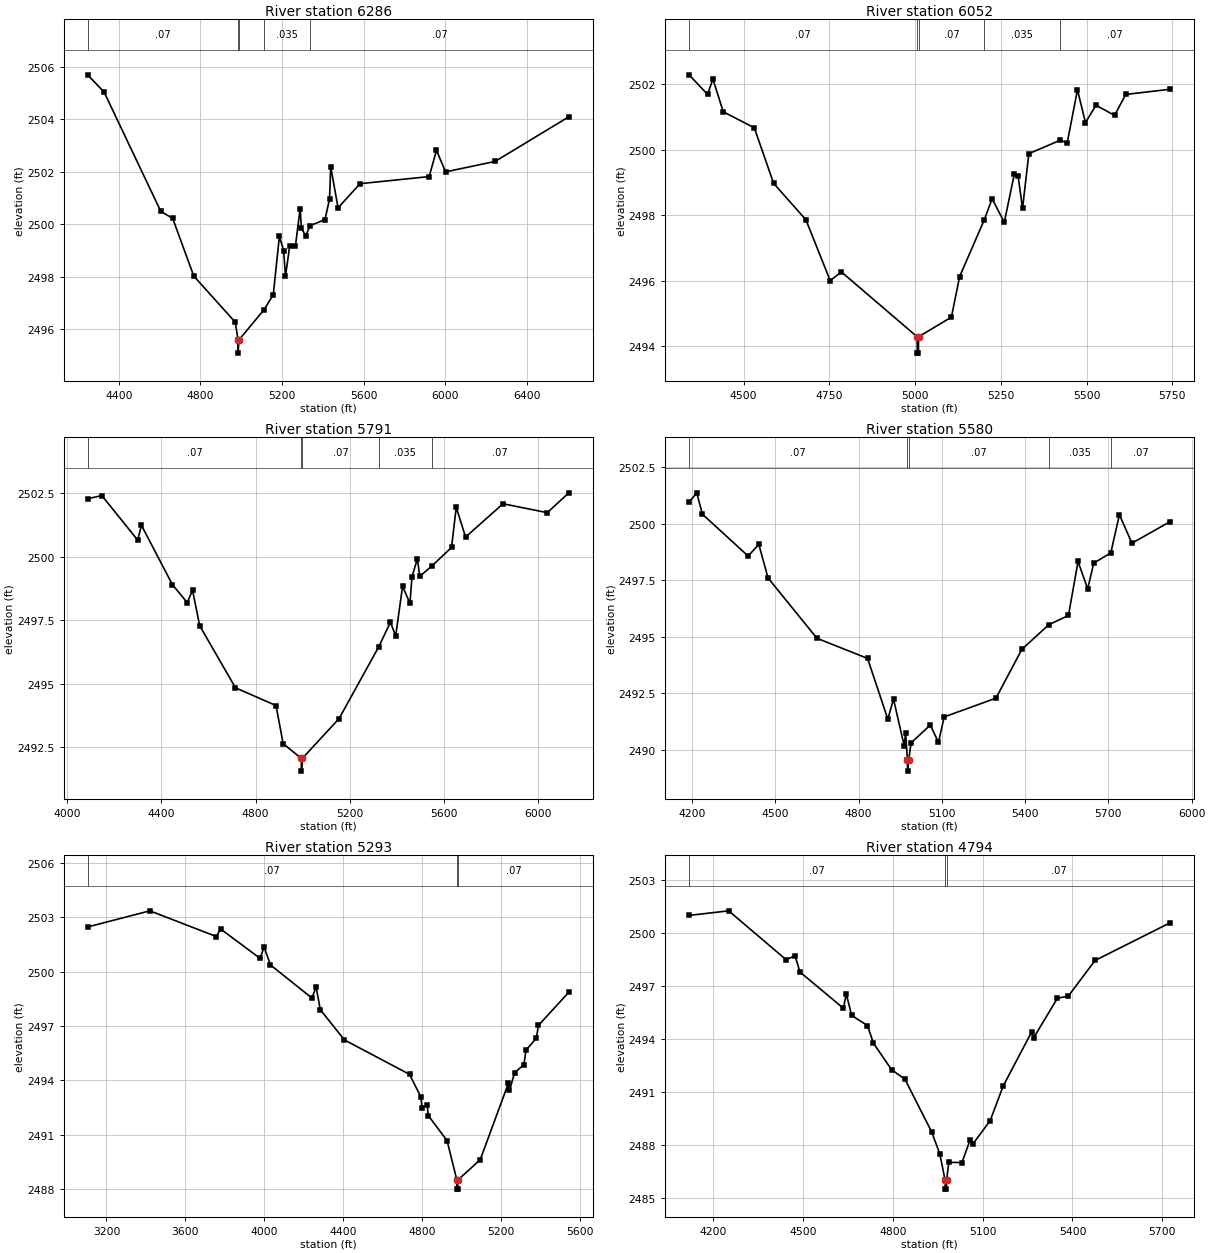
Type RM Length L Ch R = 1,6286,234,234,234
BEGIN DESCRIPTION:
Bitter Creek Trib1T2_1 12.0
END DESCRIPTION:
XS GIS Cut Line= 3
      1422055.03      6781038.02      1422705.32      6781417.87
      1423605.00      6780088.00
#Sta/Elev= 30
  4246.9 2505.70  4327.9 2505.04  4605.9 2500.49  4663.8 2500.23  4767.2 2498.03
  4970.6 2496.27  4984.3 2495.59  4984.6 2495.09  4988.3 2495.59  5112.3 2496.75
  5157.0 2497.32  5186.9 2499.54  5207.9 2499.00  5216.8 2498.02  5237.8 2499.19
  5265.5 2499.17  5288.7 2500.60  5294.8 2499.86  5315.8 2499.56  5337.4 2499.95
  5410.3 2500.18  5432.6 2500.96  5438.6 2502.19  5474.5 2500.63  5582.4 2501.55
  5921.0 2501.82  5956.9 2502.82  6001.8 2502.00  6244.6 2502.40  6605.6 2504.10
#Mann=5,-1,0
  4246.9    0.07       0  4984.3    0.07       0  4988.3    0.07       0
  5112.3   0.035       0  5337.4    0.07       0
Bank Sta=4984.3,4988.3
Exp/Cntr=0.3,0.1

Type RM Length L Ch R = 1,6052,261,261,261
BEGIN DESCRIPTION:
Bitter Creek Trib1T2_1 4454
END DESCRIPTION:
XS GIS Cut Line= 3
      1422206.03      6781517.54      1422861.43      6781585.31
      1423146.14      6780897.72
#Sta/Elev= 30
  4341.1 2502.29  4394.8 2501.69  4410.4 2502.16  4440.6 2501.16  4531.1 2500.67
  4587.5 2498.97  4681.4 2497.86  4752.3 2496.00  4785.3 2496.26  5005.9 2494.28
  5006.2 2493.78  5009.7 2493.78  5009.9 2494.28  5105.8 2494.88  5129.7 2496.12
  5201.8 2497.86  5224.4 2498.50  5260.0 2497.78  5289.3 2499.26  5300.1 2499.20
  5313.2 2498.21  5331.6 2499.88  5423.1 2500.29  5443.4 2500.21  5473.3 2501.83
  5496.6 2500.83  5527.4 2501.36  5581.5 2501.05  5614.0 2501.69  5744.2 2501.85
#Mann=5,-1,0
  4341.1    0.07       0  5005.9    0.07       0  5009.9    0.07       0
  5201.8   0.035       0  5423.1    0.07       0
Bank Sta=5005.9,5009.9
Exp/Cntr=0.3,0.1

Type RM Length L Ch R = 1,5791,211,211,211
BEGIN DESCRIPTION:
Bitter Creek Trib1T2_1 11.0
END DESCRIPTION:
XS GIS Cut Line= 3
      1422105.01      6781638.00      1423006.72      6781777.29
      1423305.00      6780687.99
#Sta/Elev= 30
  4087.6 2502.28  4148.3 2502.40  4300.1 2500.65  4316.1 2501.23  4447.3 2498.90
  4510.4 2498.19  4532.8 2498.68  4563.2 2497.28  4714.9 2494.84  4887.0 2494.14
  4917.3 2492.64  4994.6 2492.06  4994.9 2491.56  4998.6 2492.06  5154.8 2493.63
  5323.3 2496.46  5372.5 2497.42  5394.7 2496.88  5424.0 2498.83  5455.5 2498.16
  5463.7 2499.19  5486.6 2499.92  5496.9 2499.22  5546.8 2499.62  5631.7 2500.36
  5651.7 2501.94  5691.4 2500.77  5850.0 2502.08  6038.0 2501.73  6129.4 2502.51
#Mann=5,-1,0
  4087.6    0.07       0  4994.6    0.07       0  4998.6    0.07       0
  5323.3   0.035       0  5546.8    0.07       0
Bank Sta=4994.6,4998.6
Exp/Cntr=0.3,0.1

Type RM Length L Ch R = 1,5580,287,287,287
BEGIN DESCRIPTION:
Bitter Creek Trib1T2_1 4455
END DESCRIPTION:
XS GIS Cut Line= 3
      1422278.94      6781741.50      1423055.54      6781972.78
      1423296.77      6781081.55
#Sta/Elev= 30
  4189.7 2500.96  4216.9 2501.37  4237.8 2500.42  4402.3 2498.57  4440.7 2499.09
  4473.9 2497.60  4650.2 2494.93  4832.5 2494.04  4905.5 2491.35  4925.9 2492.24
  4964.3 2490.18  4969.5 2490.72  4976.2 2489.55  4976.5 2489.05  4981.0 2489.55
  4989.0 2490.30  5058.6 2491.09  5087.8 2490.32  5108.5 2491.45  5295.0 2492.28
  5388.3 2494.44  5485.1 2495.53  5556.1 2495.94  5590.7 2498.33  5625.4 2497.12
  5647.3 2498.26  5708.6 2498.71  5739.8 2500.40  5784.8 2499.14  5923.3 2500.10
#Mann=5,-1,0
  4189.7    0.07       0  4976.2    0.07       0  4981.0    0.07       0
  5485.1   0.035       0  5708.6    0.07       0
Bank Sta=4976.2,4981
Exp/Cntr=0.3,0.1

Type RM Length L Ch R = 1,5293,499,499,499
BEGIN DESCRIPTION:
Bitter Creek Trib1T2_1 10.0
END DESCRIPTION:
XS GIS Cut Line= 3
      1421355.04      6781638.01      1423156.44      6782227.53
      1423671.11      6782056.95
#Sta/Elev= 30
  3104.6 2502.46  3420.2 2503.35  3756.9 2501.93  3778.0 2502.35  3977.9 2500.73
  3998.9 2501.35  4030.5 2500.37  4240.8 2498.54  4262.0 2499.15  4283.2 2497.90
  4405.4 2496.23  4735.4 2494.33  4792.9 2493.08  4798.6 2492.49  4824.8 2492.65
  4830.1 2492.06  4925.6 2490.67  4975.0 2488.50  4975.4 2488.00  4979.5 2488.00
  4979.8 2488.50  5093.3 2489.62  5236.2 2493.84  5241.5 2493.44  5267.9 2494.43
  5314.5 2494.86  5325.1 2495.66  5377.7 2496.33  5388.3 2497.03  5542.2 2498.86
#Mann=3,-1,0
  3104.6    0.07       0  4975.0    0.07       0  4979.8    0.07       0
Bank Sta=4975,4979.8
Exp/Cntr=0.3,0.1

Type RM Length L Ch R = 1,4794,484,484,484
BEGIN DESCRIPTION:
Bitter Creek Trib1T2_1 9.0
END DESCRIPTION:
XS GIS Cut Line= 3
      1422413.88      6782520.41      1423287.47      6782621.34
      1423910.64      6782247.32
#Sta/Elev= 30
  4120.6 2500.97  4252.6 2501.23  4443.9 2498.47  4474.1 2498.68  4490.4 2497.77
  4635.1 2495.72  4645.2 2496.52  4663.1 2495.31  4715.7 2494.74  4735.8 2493.74
  4796.2 2492.24  4840.9 2491.70  4929.7 2488.73  4957.2 2487.48  4975.0 2485.98
  4975.3 2485.48  4979.4 2485.48  4979.8 2485.98  4987.4 2487.00  5031.0 2486.98
  5058.2 2488.25  5067.1 2488.02  5125.4 2489.36  5168.9 2491.32  5264.2 2494.39
  5270.0 2494.03  5349.7 2496.28  5386.6 2496.41  5475.3 2498.42  5726.8 2500.56
#Mann=3,-1,0
  4120.6    0.07       0  4975.0    0.07       0  4979.8    0.07       0
Bank Sta=4975,4979.8
Exp/Cntr=0.3,0.1

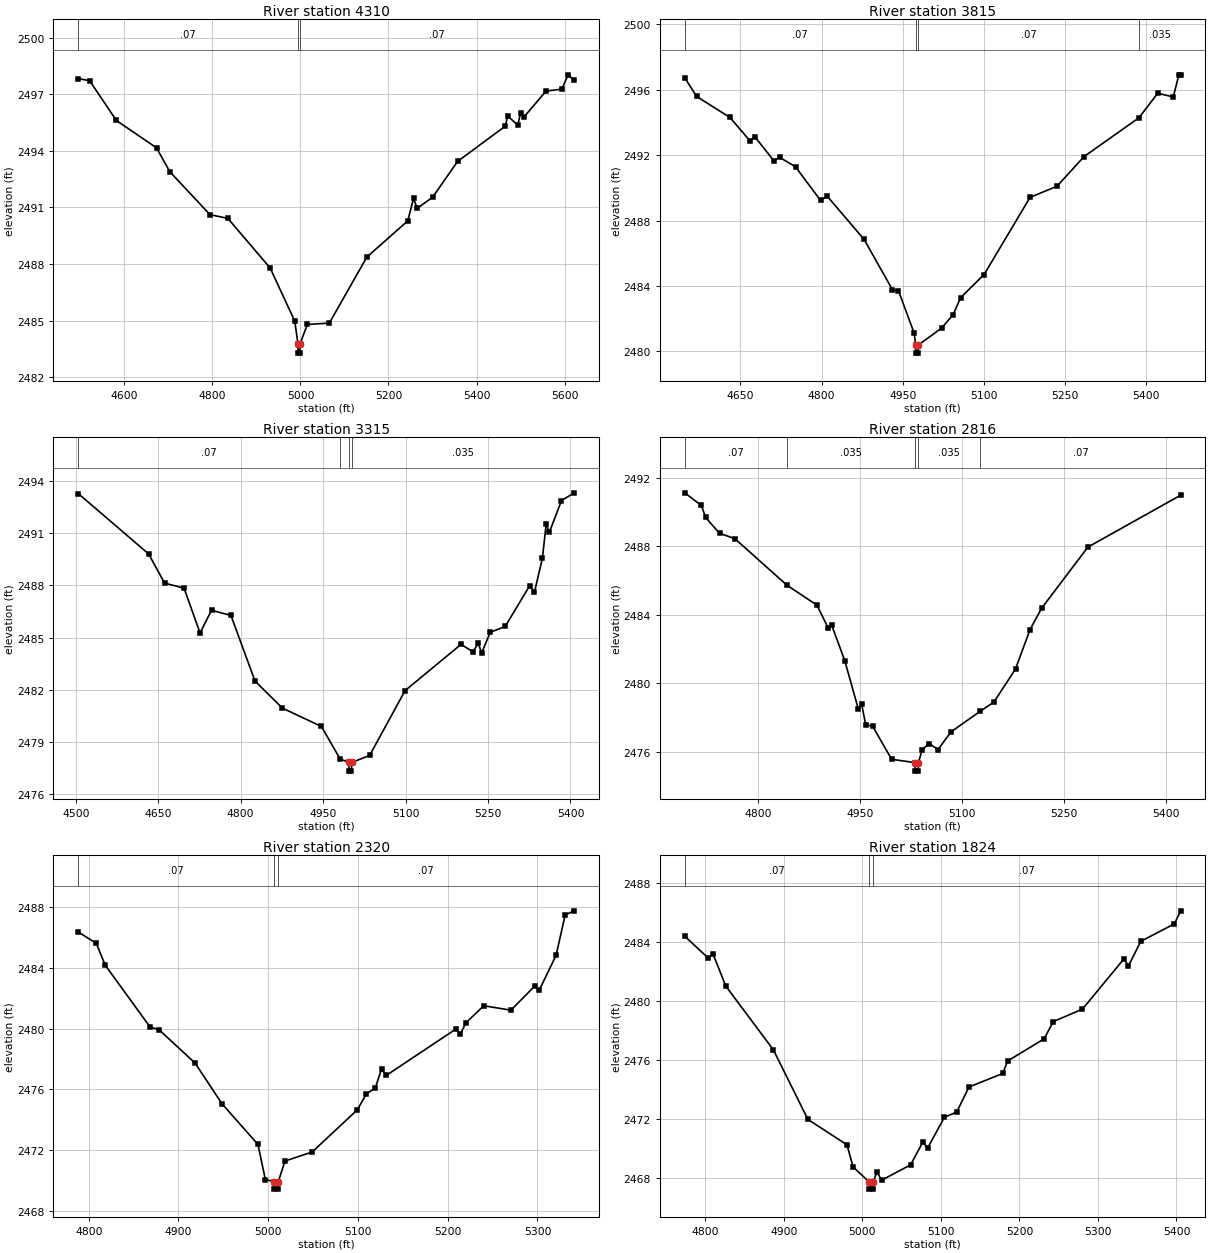
Type RM Length L Ch R = 1,4310,495,495,495
BEGIN DESCRIPTION:
Bitter Creek Trib1T2_1 8.0
END DESCRIPTION:
XS GIS Cut Line= 3
      1422929.42      6783142.81      1423427.81      6783061.95
      1423804.49      6782567.24
#Sta/Elev= 30
  4495.1 2497.83  4521.0 2497.72  4581.8 2495.61  4673.0 2494.16  4703.4 2492.89
  4794.5 2490.62  4835.1 2490.42  4931.2 2487.79  4987.0 2484.98  4994.3 2483.78
  4994.6 2483.28  4998.8 2483.28  4999.2 2483.78  5015.7 2484.80  5065.6 2484.87
  5150.8 2488.37  5243.8 2490.29  5256.9 2491.48  5265.2 2490.95  5300.5 2491.55
  5356.9 2493.44  5464.8 2495.30  5471.1 2495.84  5493.9 2495.36  5500.1 2496.03
  5507.7 2495.79  5558.0 2497.17  5593.6 2497.27  5608.2 2498.03  5621.8 2497.73
#Mann=3,-1,0
  4495.1    0.07       0  4994.3    0.07       0  4999.2    0.07       0
Bank Sta=4994.3,4999.2
Exp/Cntr=0.3,0.1

Type RM Length L Ch R = 1,3815,500,500,500
BEGIN DESCRIPTION:
Bitter Creek Trib1T2_1 7.0
END DESCRIPTION:
XS GIS Cut Line= 3
      1423355.04      6783537.98      1423767.98      6783351.73
      1424054.98      6782988.02
#Sta/Elev= 30
  4547.0 2496.75  4568.9 2495.60  4630.7 2494.31  4667.6 2492.88  4676.9 2493.12
  4711.5 2491.67  4722.5 2491.87  4751.8 2491.29  4798.1 2489.23  4810.2 2489.50
  4878.4 2486.85  4930.9 2483.77  4941.9 2483.72  4970.9 2481.12  4973.9 2480.39
  4974.3 2479.89  4978.5 2479.89  4978.9 2480.39  5021.6 2481.42  5043.0 2482.24
  5056.9 2483.29  5100.2 2484.70  5185.1 2489.42  5234.8 2490.10  5285.0 2491.92
  5386.3 2494.29  5420.9 2495.79  5449.7 2495.57  5460.1 2496.92  5463.3 2496.92
#Mann=4,-1,0
  4547.0    0.07       0  4973.9    0.07       0  4978.9    0.07       0
  5386.3   0.035       0
Bank Sta=4973.9,4978.9
Exp/Cntr=0.3,0.1

Type RM Length L Ch R = 1,3315,499,499,499
BEGIN DESCRIPTION:
Bitter Creek Trib1T2_1 6.0
END DESCRIPTION:
XS GIS Cut Line= 3
      1423655.01      6784037.99      1424050.81      6783739.73
      1424255.00      6783388.00
#Sta/Elev= 30
  4504.4 2493.28  4632.4 2489.81  4661.6 2488.13  4697.0 2487.84  4726.1 2485.26
  4746.9 2486.57  4782.3 2486.27  4826.0 2482.50  4876.0 2480.94  4946.8 2479.89
  4980.9 2478.02  4997.0 2477.82  4997.3 2477.32  5001.6 2477.32  5002.0 2477.82
  5034.6 2478.22  5099.1 2481.95  5201.0 2484.61  5222.5 2484.18  5232.4 2484.68
  5238.2 2484.10  5254.0 2485.30  5281.3 2485.64  5325.8 2487.98  5334.3 2487.59
  5348.9 2489.55  5355.8 2491.52  5361.6 2491.05  5383.6 2492.87  5406.7 2493.32
#Mann=4,-1,0
  4504.4    0.07       0  4980.9   0.035       0  4997.0   0.035       0
  5002.0   0.035       0
Bank Sta=4997,5002
Exp/Cntr=0.3,0.1

Type RM Length L Ch R = 1,2816,496,496,496
BEGIN DESCRIPTION:
Bitter Creek Trib1T2_1 5.0
END DESCRIPTION:
XS GIS Cut Line= 3
      1423804.98      6784288.00      1424105.39      6784222.84
      1424504.96      6784088.01
#Sta/Elev= 30
  4692.6 2491.12  4717.2 2490.38  4723.3 2489.68  4743.8 2488.76  4766.4 2488.44
  4843.0 2485.72  4887.0 2484.56  4903.6 2483.22  4908.8 2483.38  4928.0 2481.31
  4947.7 2478.51  4952.8 2478.76  4958.7 2477.58  4968.9 2477.48  4996.9 2475.55
  5031.0 2475.36  5031.4 2474.86  5035.9 2474.86  5036.3 2475.36  5041.8 2476.12
  5052.4 2476.46  5065.1 2476.12  5084.0 2477.15  5127.2 2478.36  5147.3 2478.90
  5179.0 2480.83  5200.1 2483.11  5217.2 2484.37  5285.4 2487.95  5421.7 2490.98
#Mann=5,-1,0
  4692.6    0.07       0  4843.0   0.035       0  5031.0   0.035       0
  5036.3   0.035       0  5127.2    0.07       0
Bank Sta=5031,5036.3
Exp/Cntr=0.3,0.1

Type RM Length L Ch R = 1,2320,496,496,496
BEGIN DESCRIPTION:
Bitter Creek Trib1T2_1 4.0
END DESCRIPTION:
XS GIS Cut Line= 3
      1423904.95      6784638.00      1424116.42      6784628.07
      1424454.96      6784588.01
#Sta/Elev= 30
  4788.3 2486.37  4808.4 2485.62  4818.4 2484.18  4868.4 2480.11  4878.4 2479.93
  4918.5 2477.74  4948.5 2475.06  4988.6 2472.38  4996.8 2470.07  5005.9 2469.94
  5006.4 2469.44  5010.9 2469.44  5011.3 2469.94  5018.7 2471.29  5048.9 2471.88
  5099.3 2474.66  5109.3 2475.70  5119.4 2476.11  5126.3 2477.35  5131.4 2476.92
  5209.2 2479.98  5214.2 2479.64  5220.1 2480.38  5240.2 2481.51  5270.5 2481.22
  5297.0 2482.81  5302.0 2482.53  5320.8 2484.84  5330.9 2487.49  5340.9 2487.76
#Mann=3,-1,0
  4788.3    0.07       0  5005.9    0.07       0  5011.3    0.07       0
Bank Sta=5005.9,5011.3
Exp/Cntr=0.3,0.1

Type RM Length L Ch R = 1,1824,419,419,419
BEGIN DESCRIPTION:
Bitter Creek Trib1T2_1 3.0
END DESCRIPTION:
XS GIS Cut Line= 3
      1423904.96      6784987.98      1424105.43      6785093.18
      1424454.97      6784888.02
#Sta/Elev= 30
  4773.6 2484.42  4803.9 2482.92  4809.6 2483.23  4826.0 2481.03  4886.5 2476.71
  4930.6 2471.98  4980.3 2470.26  4988.2 2468.75  5008.4 2467.75  5008.8 2467.25
  5013.4 2467.25  5013.8 2467.75  5018.5 2468.43  5024.3 2467.85  5061.4 2468.90
  5077.1 2470.46  5082.9 2470.02  5104.4 2472.13  5120.1 2472.48  5135.7 2474.18
  5178.7 2475.10  5185.0 2475.95  5231.4 2477.45  5243.1 2478.62  5280.3 2479.47
  5333.1 2482.88  5338.9 2482.41  5354.6 2484.07  5397.5 2485.26  5405.3 2486.14
#Mann=3,-1,0
  4773.6    0.07       0  5008.4    0.07       0  5013.8    0.07       0
Bank Sta=5008.4,5013.8
Exp/Cntr=0.3,0.1

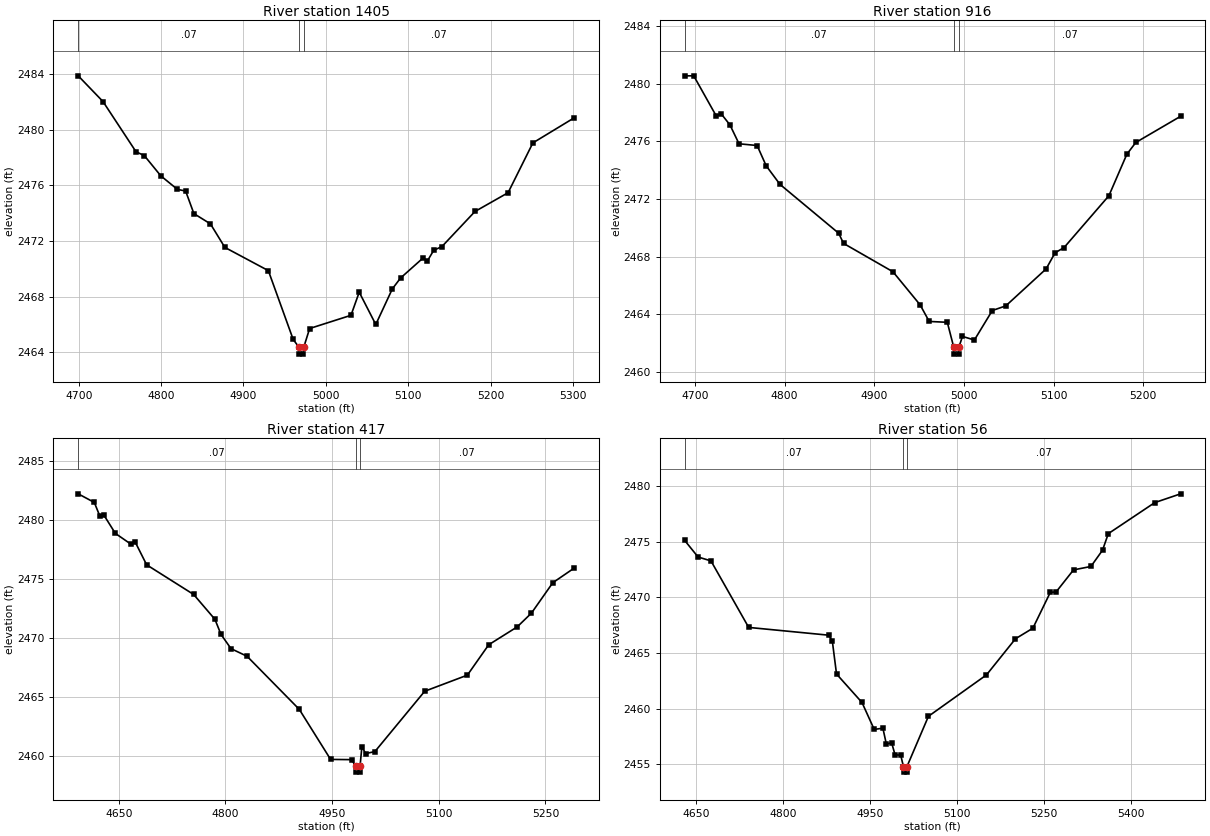
Type RM Length L Ch R = 1,1405,489,489,489
BEGIN DESCRIPTION:
Bitter Creek Trib1T2_1 2.0
END DESCRIPTION:
XS GIS Cut Line= 3
      1423755.04      6785488.00      1424054.60      6785463.00
      1424354.96      6785438.00
#Sta/Elev= 30
  4699.4 2483.87  4729.5 2482.02  4769.6 2478.41  4779.6 2478.14  4799.7 2476.68
  4819.8 2475.71  4829.8 2475.59  4839.8 2473.97  4859.9 2473.23  4877.4 2471.54
  4930.2 2469.87  4960.3 2464.93  4967.3 2464.37  4967.8 2463.87  4972.7 2463.87
  4973.2 2464.37  4980.3 2465.71  5030.5 2466.66  5040.5 2468.32  5060.6 2466.00
  5080.7 2468.56  5090.7 2469.34  5118.2 2470.79  5123.2 2470.56  5130.9 2471.33
  5140.9 2471.60  5181.0 2474.12  5221.2 2475.47  5251.3 2479.05  5301.4 2480.85
#Mann=3,-1,0
  4699.4    0.07       0  4967.3    0.07       0  4973.2    0.07       0
Bank Sta=4967.3,4973.2
Exp/Cntr=0.3,0.1

Type RM Length L Ch R = 1,916,499,499,499
BEGIN DESCRIPTION:
Bitter Creek Trib1T2_1 1.0
END DESCRIPTION:
XS GIS Cut Line= 3
      1423805.03      6785838.00      1424113.44      6785881.81
      1424354.96      6785888.00
#Sta/Elev= 30
  4688.5 2480.55  4698.6 2480.55  4723.9 2477.74  4729.0 2477.93  4739.0 2477.14
  4749.1 2475.83  4769.3 2475.71  4779.4 2474.30  4794.8 2473.01  4860.2 2469.62
  4865.7 2468.91  4920.8 2466.94  4951.1 2464.64  4961.2 2463.49  4981.4 2463.43
  4988.5 2461.72  4989.0 2461.22  4993.9 2461.22  4994.4 2461.72  4998.3 2462.45
  5011.6 2462.20  5031.6 2464.25  5046.6 2464.57  5091.6 2467.14  5101.6 2468.26
  5111.6 2468.62  5161.6 2472.22  5181.6 2475.10  5191.6 2475.92  5241.6 2477.74
#Mann=3,-1,0
  4688.5    0.07       0  4988.5    0.07       0  4994.4    0.07       0
Bank Sta=4988.5,4994.4
Exp/Cntr=0.3,0.1

Type RM Length L Ch R = 1,417,361,361,361
BEGIN DESCRIPTION:
Bitter Creek Trib1T2_1 0.1
END DESCRIPTION:
XS GIS Cut Line= 3
      1423605.03      6786138.01      1423964.88      6786327.95
      1424255.00      6786338.00
#Sta/Elev= 30
  4593.1 2482.25  4615.7 2481.52  4623.3 2480.39  4628.9 2480.47  4645.3 2478.89
  4667.3 2477.97  4673.0 2478.18  4689.3 2476.22  4755.4 2473.70  4785.3 2471.59
  4793.8 2470.31  4807.9 2469.10  4830.5 2468.45  4903.9 2463.94  4947.9 2459.69
  4977.5 2459.67  4983.3 2459.11  4983.8 2458.61  4988.8 2458.61  4989.3 2459.11
  4991.9 2460.77  4997.2 2460.19  5010.1 2460.35  5080.2 2465.48  5140.2 2466.85
  5170.2 2469.43  5210.3 2470.95  5230.3 2472.12  5260.3 2474.70  5290.3 2475.94
#Mann=3,-1,0
  4593.1    0.07       0  4983.3    0.07       0  4989.3    0.07       0
Bank Sta=4983.3,4989.3
Exp/Cntr=0.3,0.1

Type RM Length L Ch R = 1,56,0,0,0
BEGIN DESCRIPTION:
Bitter Creek Trib1T2_1 4300
END DESCRIPTION:
XS GIS Cut Line= 3
      1423639.48      6786340.29      1423844.52      6786647.80
      1424329.59      6786642.35
#Sta/Elev= 30
  4630.4 2475.11  4653.5 2473.62  4675.7 2473.27  4740.7 2467.29  4878.9 2466.59
  4884.9 2466.04  4892.1 2463.10  4936.0 2460.54  4957.0 2458.12  4972.0 2458.23
  4978.0 2456.79  4987.0 2456.93  4993.0 2455.83  5002.7 2455.81  5007.4 2454.78
  5007.9 2454.28  5013.0 2454.28  5013.5 2454.78  5050.5 2459.30  5150.5 2463.02
  5200.5 2466.27  5230.5 2467.22  5260.5 2470.44  5270.5 2470.48  5300.5 2472.46
  5330.5 2472.77  5350.5 2474.23  5360.5 2475.72  5440.5 2478.51  5485.1 2479.30
#Mann=3,-1,0
  4630.4    0.07       0  5007.4    0.07       0  5013.5    0.07       0
Bank Sta=5007.4,5013.5
Exp/Cntr=0.3,0.1

Chan Stop Cuts=-1