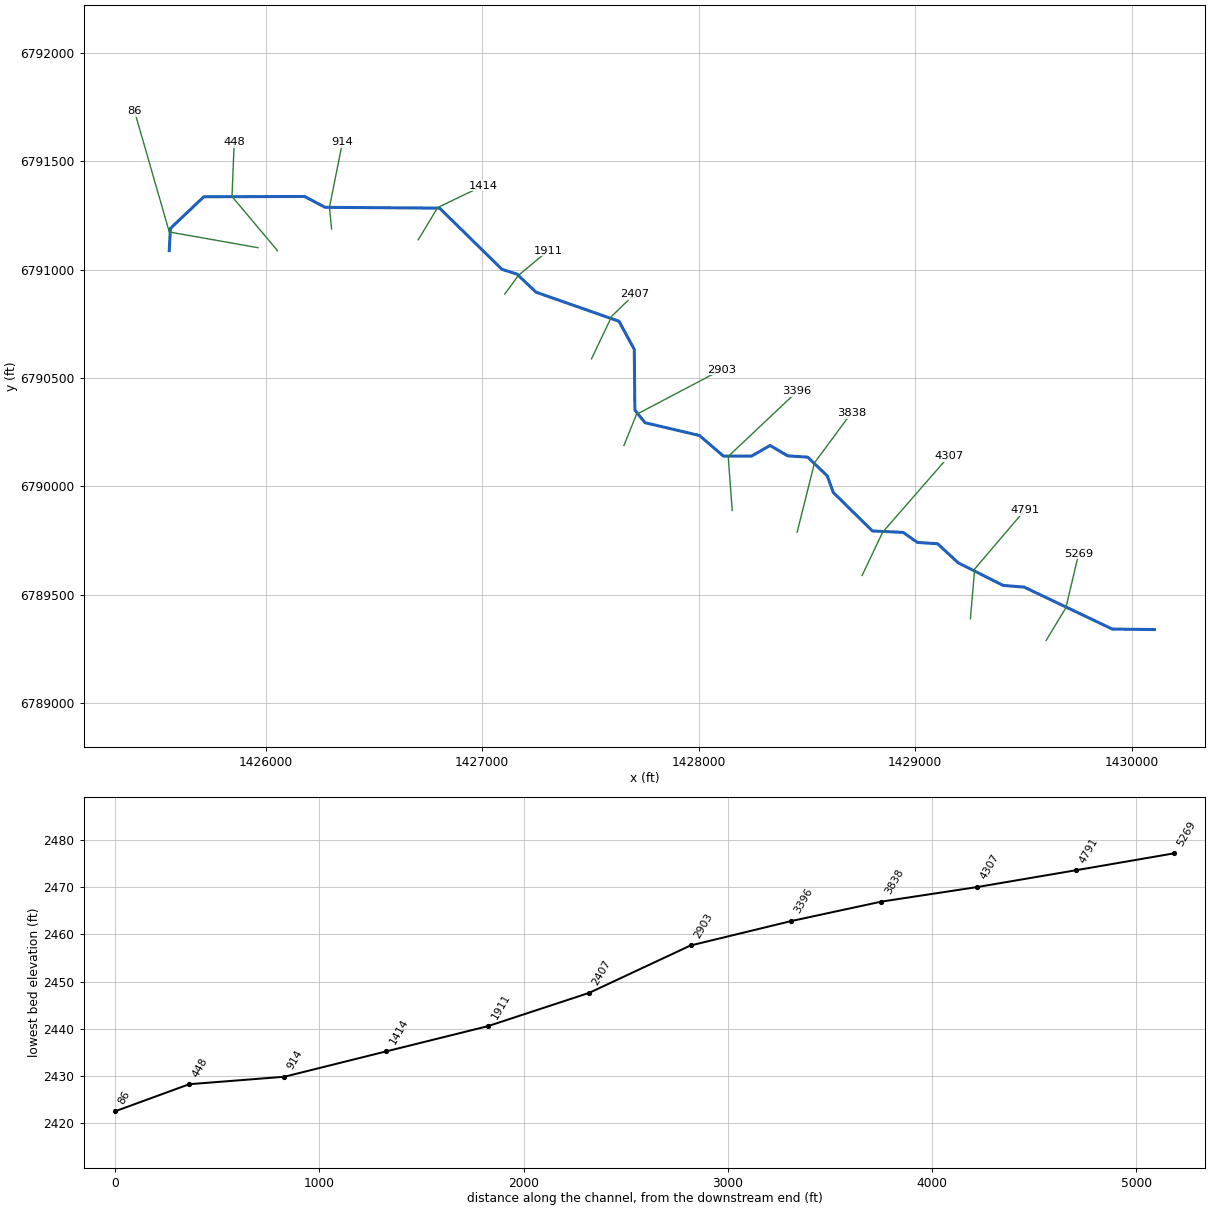
--- Bitter Creek Trib2.prj (project) ---

Proj Title=Bitter Creek Trib2 Base Level Engineering
Current Plan=p01
Default Exp/Contr=0.3,0.1
English Units
Geom File=g01
Flow File=f01
Plan File=p01
Y Axis Title=Elevation
X Axis Title(PF)=Main Channel Distance
X Axis Title(XS)=Station
BEGIN DESCRIPTION:
Bitter Creek Trib2
END DESCRIPTION:
DSS Export Rating Curves= 0
DSS Export Rating Curve Sorted= 0
DSS Export Volume Flow Curves= 0
DXF OffsetX= 0
DXF OffsetY= 0
DXF ScaleX= 1
DXF ScaleY= 10

--- Bitter Creek Trib2.p01 (plan) ---

Plan Title=Multiple Run
Short Identifier=Multiple
Geom File=g01
Flow File=f01
Subcritical Flow
K Sum by GR= 0
Std Step Tol= 0.01
Critical Tol= 0.01
Num of Std Step Trials= 20
Max Error Tol= 0.3
Flow Tol Ratio= 0.001
Split Flow NTrial= 30
Split Flow Tol= 0.02
Split Flow Ratio= 0.02
Log Output Level= 0
Friction Slope Method= 1
Unsteady Friction Slope Method= 2
Unsteady Bridges Friction Slope Method= 1
Parabolic Critical Depth
Global Vel Dist=  1 , 1 , 1
Global Log Level= 0
CheckData=True
Encroach Param= -1, 0, 0, 0
BEGIN DESCRIPTION:
Multiple Run
END DESCRIPTION:

--- Bitter Creek Trib2.f01 (steady flow) ---

Flow Title=Multiple
Program Version=4.10
Number of Profiles= 7
Profile Names=10-year,25-year,50-year,1pct_min,100-year,1pct_plu,500-year
River Rch & RM=Bitter Creek Tri,Reach-1         ,5269
     153     201     239     141     281     560     392
River Rch & RM=Bitter Creek Tri,Reach-1         ,4791
     326     456     563     345     689    1374    1045
Boundary for River Rch & Prof#=Bitter Creek Tri,Reach-1         , 1
Up Type= 0
Dn Type= 3
Dn Slope=0.014
Boundary for River Rch & Prof#=Bitter Creek Tri,Reach-1         , 2
Up Type= 0
Dn Type= 3
Dn Slope=0.014
Boundary for River Rch & Prof#=Bitter Creek Tri,Reach-1         , 3
Up Type= 0
Dn Type= 3
Dn Slope=0.014
Boundary for River Rch & Prof#=Bitter Creek Tri,Reach-1         , 4
Up Type= 0
Dn Type= 3
Dn Slope=0.014
Boundary for River Rch & Prof#=Bitter Creek Tri,Reach-1         , 5
Up Type= 0
Dn Type= 3
Dn Slope=0.014
Boundary for River Rch & Prof#=Bitter Creek Tri,Reach-1         , 6
Up Type= 0
Dn Type= 3
Dn Slope=0.014
Boundary for River Rch & Prof#=Bitter Creek Tri,Reach-1         , 7
Up Type= 0
Dn Type= 3
Dn Slope=0.014
DSS Import GetInterval= 0
DSS Import GetPeak= 0
DSS Import FillOption= 0

--- Bitter Creek Trib2.g01 (geometry) ---

Geom Title=Existing Conditions
Program Version=4.10

River Reach=Bitter Creek Tri,Reach-1
Reach XY= 30
        1430105.        6789338.      1429910.52      6789340.35
      1429503.42      6789534.17      1429406.58      6789541.83
      1429198.95      6789646.16       1429103.5      6789734.38
      1429010.57      6789740.47      1428944.49      6789786.77
      1428802.55      6789793.47      1428621.65      6789971.33
      1428594.23       6790047.7      1428503.52      6790134.39
      1428410.97      6790140.38        1428330.       6790188.4
       1428244.5      6790139.23       1428114.6       6790139.2
       1428003.5      6790234.38      1427752.29       6790293.4
      1427705.47      6790351.71      1427702.76      6790632.07
      1427632.19      6790761.95      1427248.95      6790896.16
      1427161.04      6790979.82      1427091.79      6791001.63
      1426803.54      6791284.46      1426275.03      6791288.07
      1426180.08       6791338.2      1425714.59       6791336.8
      1425560.35       6791190.5        1425555.        6791088.

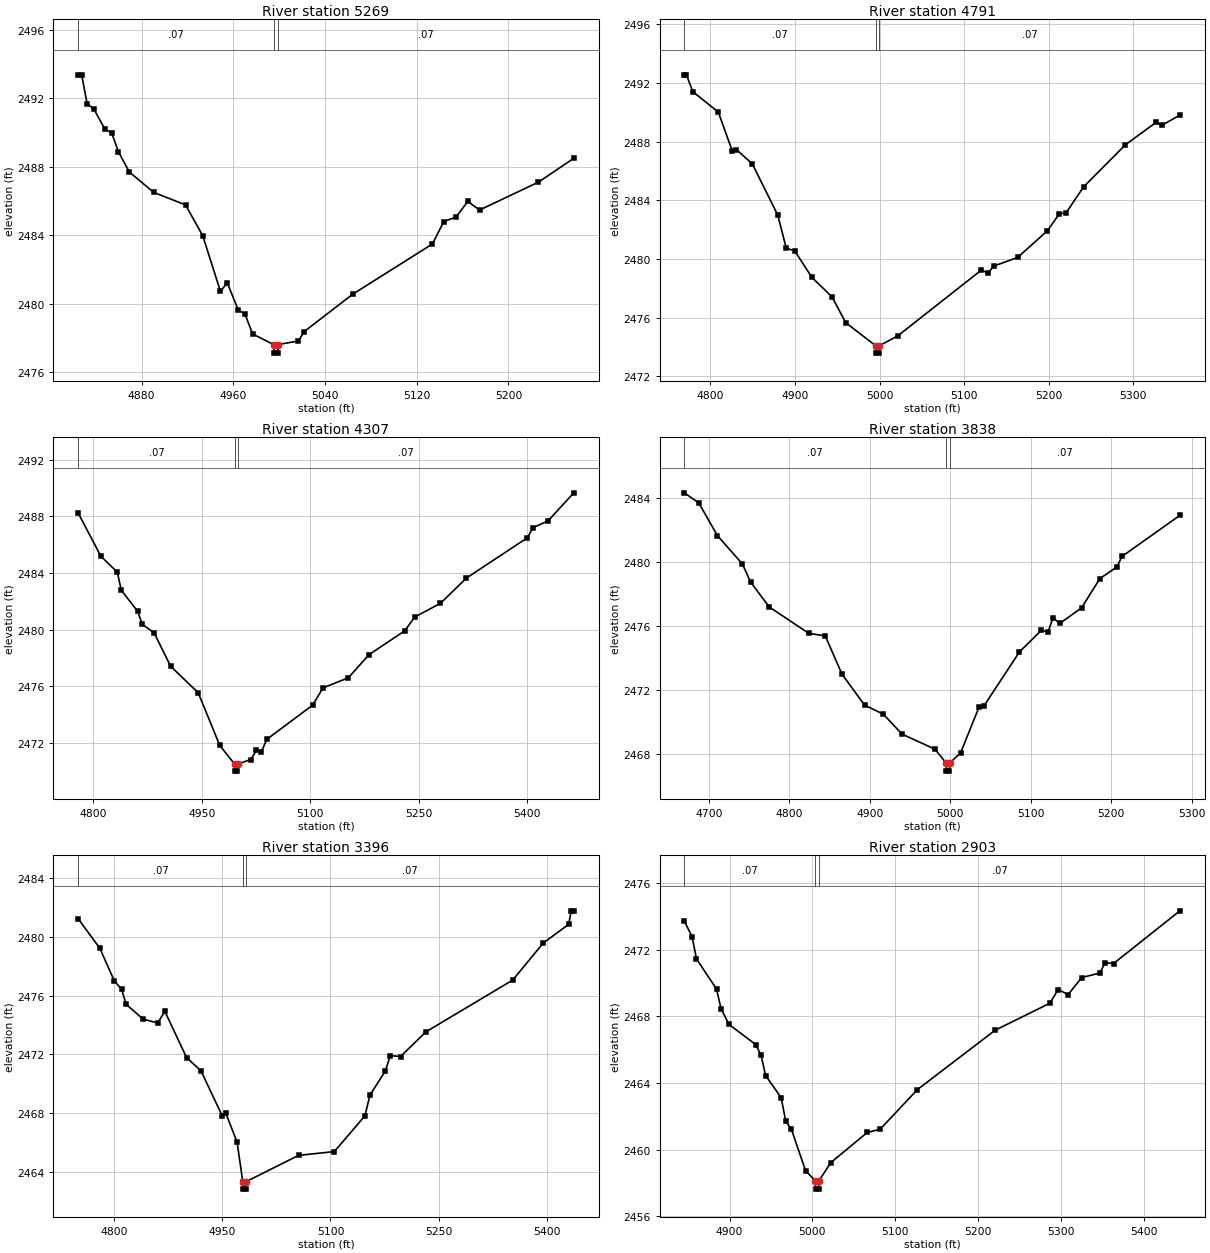
Type RM Length L Ch R = 1 ,5269    ,478,478,478
BEGIN DESCRIPTION:
Bitter Creek Trib2 10.0
END DESCRIPTION:
XS GIS Cut Line= 3
      1429604.98      6789287.97      1429695.86      6789437.88
        1429755.      6789687.98
#Sta/Elev= 30
  4824.7 2493.37  4827.7 2493.37  4832.5 2491.69  4838.3 2491.38    4848  2490.2
  4853.8    2490  4859.8 2488.88  4869.3  2487.7  4890.6 2486.51  4918.3 2485.78
  4933.3 2483.99  4948.8 2480.73  4954.7 2481.24  4964.3 2479.65  4970.2 2479.41
  4976.8 2478.25  4995.1 2477.63  4995.4 2477.13  4998.9 2477.13  4999.1 2477.63
  5016.8 2477.84  5021.9 2478.39  5064.2 2480.57  5133.7  2483.5  5143.6 2484.81
  5154.3 2485.07  5164.5 2485.98  5174.8 2485.48  5226.2 2487.11    5257  2488.5
#Mann= 3 ,-1 , 0
  4824.7     .07       0  4995.1     .07       0  4999.1     .07       0
Bank Sta=4995.1,4999.1
XS Rating Curve= 0 ,0
Exp/Cntr=0.3,0.1

Type RM Length L Ch R = 1 ,4791    ,484,484,484
BEGIN DESCRIPTION:
Bitter Creek Trib2 9.0
END DESCRIPTION:
XS GIS Cut Line= 3
        1429255.      6789387.98      1429274.93      6789617.82
      1429505.02      6789888.02
#Sta/Elev= 30
  4769.3 2492.56  4771.8 2492.56  4779.4 2491.41  4809.5 2490.02  4825.9 2487.38
  4830.9 2487.46  4849.6 2486.49  4879.7    2483  4889.8 2480.73  4899.8 2480.55
  4919.9 2478.75    4944  2477.4    4960 2475.65  4995.6 2474.07  4995.8 2473.57
  4999.3 2473.57  4999.6 2474.07  5021.6 2474.75  5120.4 2479.24  5128.1 2479.03
  5134.7  2479.5  5163.2  2480.1  5198.4 2481.92  5212.6 2483.09  5220.4 2483.14
  5241.2 2484.92  5290.6 2487.79  5326.9 2489.32  5333.4 2489.11  5354.9 2489.81
#Mann= 3 ,-1 , 0
  4769.3     .07       0  4995.6     .07       0  4999.6     .07       0
Bank Sta=4995.6,4999.6
XS Rating Curve= 0 ,0
Exp/Cntr=0.3,0.1

Type RM Length L Ch R = 1 ,4307    ,469,469,469
BEGIN DESCRIPTION:
Bitter Creek Trib2 8.0
END DESCRIPTION:
XS GIS Cut Line= 3
      1428754.98      6789587.97      1428849.83      6789787.58
      1429155.02      6790138.02
#Sta/Elev= 30
    4779 2488.23  4810.4 2485.18  4833.1 2484.06  4838.6 2482.79  4861.3 2481.29
  4867.6 2480.38  4884.1 2479.77  4906.8 2477.42  4945.1 2475.54  4974.9 2471.82
  4995.4 2470.51  4995.7 2470.01  4999.3 2470.01  4999.5 2470.51    5018 2470.83
  5025.6 2471.49  5032.2 2471.33  5039.8 2472.25  5103.4 2474.67  5117.7 2475.89
  5152.8  2476.6  5181.3 2478.23  5230.6 2479.91  5244.9  2480.9    5280 2481.85
  5316.1 2483.64  5400.6 2486.49  5408.2  2487.2  5429.1 2487.68  5464.7 2489.66
#Mann= 3 ,-1 , 0
    4779     .07       0  4995.4     .07       0  4999.5     .07       0
Bank Sta=4995.4,4999.5
XS Rating Curve= 0 ,0
Exp/Cntr=0.3,0.1

Type RM Length L Ch R = 1 ,3838    ,442,442,442
BEGIN DESCRIPTION:
Bitter Creek Trib2 7.0
END DESCRIPTION:
XS GIS Cut Line= 3
        1428455.      6789788.01      1428535.27      6790108.51
      1428704.98      6790337.97
#Sta/Elev= 30
  4669.6 2484.34  4687.6 2483.71  4710.8 2481.66  4741.8 2479.89  4752.1 2478.75
  4775.2  2477.2  4824.2 2475.55  4844.8 2475.39  4865.5    2473  4893.6 2471.06
    4917 2470.49    4940 2469.25  4981.2  2468.3  4995.1 2467.43  4995.4 2466.93
    4999 2466.93  4999.3 2467.43    5013 2468.08    5036 2470.96  5042.2 2471.03
  5086.1 2474.39  5113.2 2475.73  5121.6 2475.65  5127.8 2476.52  5136.2 2476.17
  5163.3 2477.15  5185.9 2478.97  5207.2 2479.71  5213.4 2480.36  5285.4 2482.93
#Mann= 3 ,-1 , 0
  4669.6     .07       0  4995.1     .07       0  4999.3     .07       0
Bank Sta=4995.1,4999.3
XS Rating Curve= 0 ,0
Exp/Cntr=0.3,0.1

Type RM Length L Ch R = 1 ,3396    ,493,493,493
BEGIN DESCRIPTION:
Bitter Creek Trib2 6.0
END DESCRIPTION:
XS GIS Cut Line= 3
        1428155.      6789887.98      1428136.64      6790137.51
      1428455.02      6790438.02
#Sta/Elev= 30
  4749.8 2481.24  4779.9 2479.22    4800    2477    4810 2476.43  4816.5  2475.4
  4840.1 2474.39  4860.1 2474.14  4870.1 2474.93  4900.2 2471.78  4920.3 2470.87
  4949.8  2467.8  4954.8 2467.97  4970.4 2466.01  4978.3 2463.31  4978.6 2462.81
  4982.3 2462.81  4982.5 2463.31  5055.7 2465.11  5105.4 2465.37  5147.9 2467.81
  5154.8 2469.22  5176.2 2470.86  5183.1 2471.91  5197.3 2471.85  5232.5 2473.53
    5353 2477.06  5395.5 2479.59  5430.7 2480.86  5434.3 2481.78  5437.8 2481.78
#Mann= 3 ,-1 , 0
  4749.8     .07       0  4978.3     .07       0  4982.5     .07       0
Bank Sta=4978.3,4982.5
XS Rating Curve= 0 ,0
Exp/Cntr=0.3,0.1

Type RM Length L Ch R = 1 ,2903    ,496,496,496
BEGIN DESCRIPTION:
Bitter Creek Trib2 5.0
END DESCRIPTION:
XS GIS Cut Line= 3
      1427655.01      6790188.04      1427712.67      6790331.48
      1428105.03      6790538.02
#Sta/Elev= 30
  4845.4 2473.72  4854.8 2472.78  4860.1 2471.45  4884.3 2469.64  4889.7 2468.47
  4899.3 2467.52  4931.6 2466.31  4938.1 2465.66  4943.5 2464.45  4962.3 2463.13
  4967.7 2461.73  4974.7 2461.22  4991.8 2458.74  5003.6 2458.14  5003.9 2457.64
  5007.6 2457.64  5007.9 2458.14  5022.2 2459.23  5066.2 2461.04  5081.7 2461.23
  5126.7 2463.61  5220.5 2467.17  5286.6 2468.79  5296.5 2469.61  5308.6 2469.31
    5325 2470.33    5347  2470.6    5353 2471.22  5363.4 2471.17  5443.4 2474.33
#Mann= 3 ,-1 , 0
  4845.4     .07       0  5003.6     .07       0  5007.9     .07       0
Bank Sta=5003.6,5007.9
XS Rating Curve= 0 ,0
Exp/Cntr=0.3,0.1

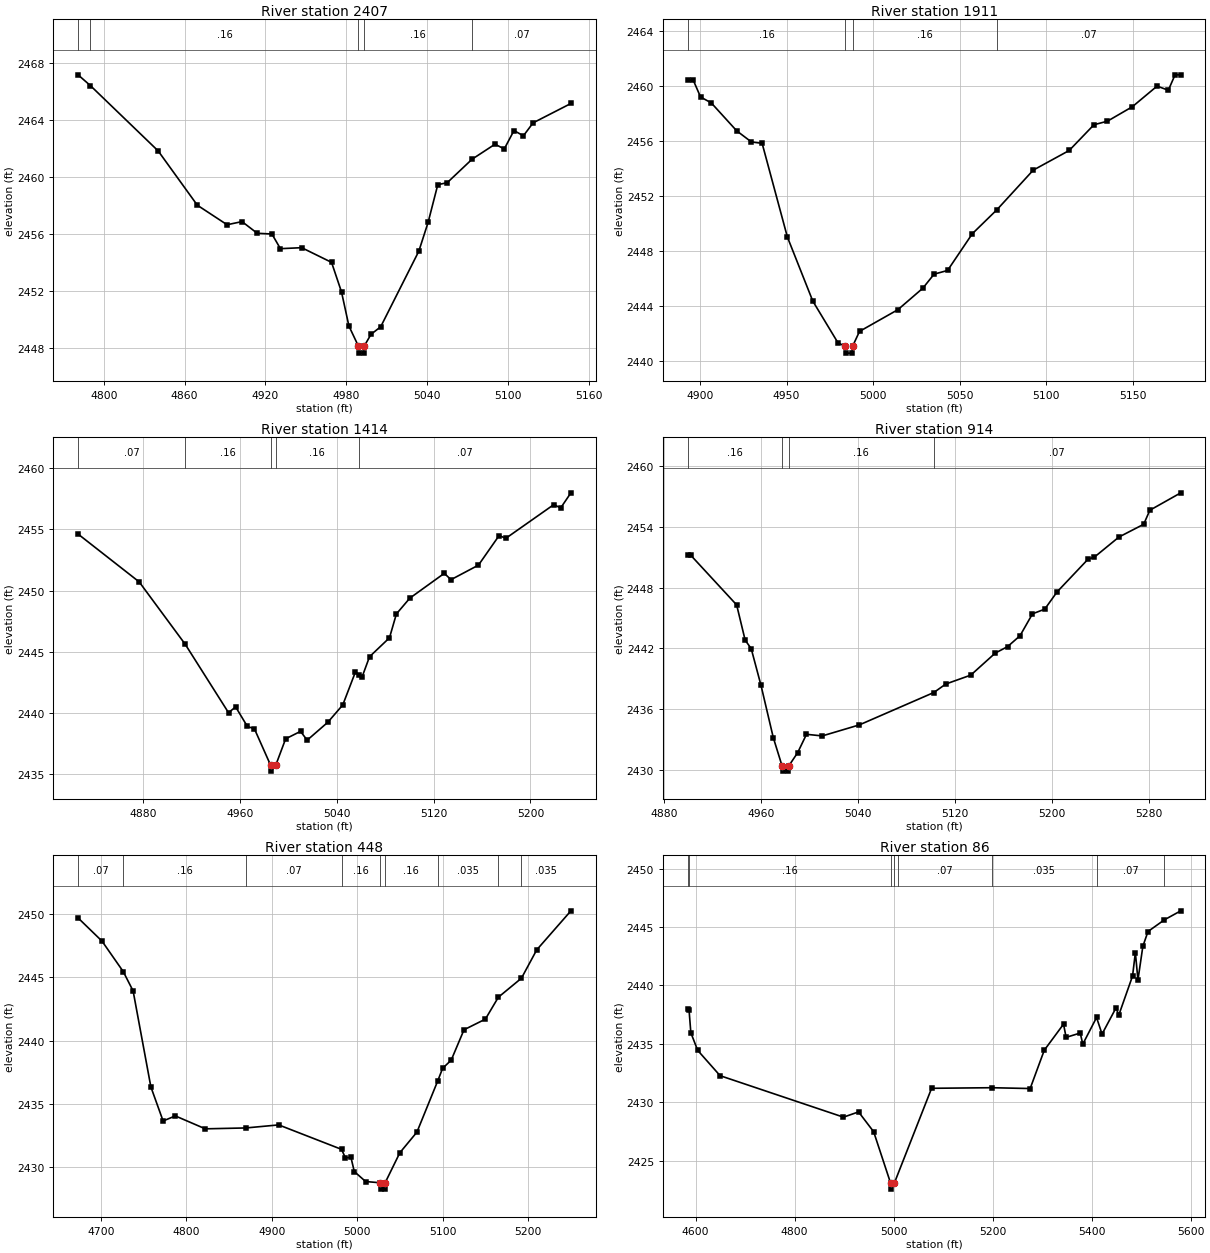
Type RM Length L Ch R = 1 ,2407    ,496,496,496
BEGIN DESCRIPTION:
Bitter Creek Trib2 4.0
END DESCRIPTION:
XS GIS Cut Line= 3
      1427505.02      6790588.03      1427599.29      6790785.93
      1427704.97      6790887.97
#Sta/Elev= 30
  4780.8 2467.15    4790 2466.39  4840.3 2461.81  4869.4    2458  4891.5 2456.63
  4902.6 2456.85  4913.9 2456.03  4924.8 2455.98  4931.1 2454.95  4946.9 2455.02
  4969.1 2453.99  4976.5 2451.91    4982 2449.52    4989 2448.12  4989.3 2447.62
  4993.1 2447.62  4993.4 2448.12  4998.4 2448.94  5005.6 2449.47  5033.9 2454.77
  5040.8 2456.79    5048 2459.44    5055 2459.58  5073.5 2461.23  5090.5 2462.28
  5097.4 2461.95  5104.6 2463.24  5111.6 2462.87  5118.8 2463.78  5146.9 2465.14
#Mann= 5 ,-1 , 0
  4780.8     .07       0    4790     .16       0    4989     .07       0
  4993.4     .16       0  5073.5     .07       0
Bank Sta=4989,4993.4
XS Rating Curve= 0 ,0
Exp/Cntr=0.3,0.1

Type RM Length L Ch R = 1 ,1911    ,497,497,497
BEGIN DESCRIPTION:
Bitter Creek Trib2 3.0
END DESCRIPTION:
XS GIS Cut Line= 3
        1427105.        6790888.       1427168.2      6790974.34
      1427305.03      6791088.03
#Sta/Elev= 30
    4893 2460.41  4896.1 2460.41  4900.3 2459.19  4906.5 2458.76  4921.2 2456.73
  4929.7 2455.92  4935.9 2455.82  4950.5 2449.01  4965.2 2444.35  4979.7 2441.33
  4983.8 2441.07  4984.1 2440.57  4987.9 2440.57  4988.2 2441.07  4992.2 2442.15
  5014.4 2443.73  5028.8 2445.29  5035.3 2446.31  5043.1 2446.58  5057.4 2449.25
  5071.6 2450.99  5092.6 2453.87  5113.4  2455.3  5127.7 2457.17  5135.5 2457.43
  5149.9 2458.48  5164.2 2459.98  5170.7 2459.68  5174.6  2460.8  5177.9  2460.8
#Mann= 4 ,-1 , 0
    4893     .16       0  4983.8     .07       0  4988.2     .16       0
  5071.6     .07       0
Bank Sta=4983.8,4988.2
XS Rating Curve= 0 ,0
Exp/Cntr=0.3,0.1

Type RM Length L Ch R = 1 ,1414    ,500,500,500
BEGIN DESCRIPTION:
Bitter Creek Trib2 2.0
END DESCRIPTION:
XS GIS Cut Line= 3
        1426705.      6791138.01      1426794.57      6791286.95
      1427004.97      6791387.98
#Sta/Elev= 30
  4826.2 2454.62  4876.7 2450.71  4914.8  2445.6  4950.5 2440.02  4956.4 2440.49
  4966.1 2438.89  4971.9  2438.7  4985.2 2435.74  4985.5 2435.24  4989.6 2435.74
  4997.7 2437.88    5010 2438.49  5015.5 2437.77  5032.6 2439.24  5044.9 2440.65
  5055.3 2443.33    5058 2443.13  5060.8 2442.92    5067 2444.59  5083.5 2446.14
  5089.2 2448.09  5100.3 2449.38  5128.8 2451.41  5134.3 2450.89    5157 2452.08
  5174.1  2454.5  5179.6 2454.27  5219.3 2457.03  5224.9 2456.75  5233.4 2457.99
#Mann= 5 ,-1 , 0
  4826.2     .07       0  4914.8     .16       0  4985.2     .07       0
  4989.6     .16       0    5058     .07       0
Bank Sta=4985.2,4989.6
XS Rating Curve= 0 ,0
Exp/Cntr=0.3,0.1

Type RM Length L Ch R = 1 ,914     ,466,466,466
BEGIN DESCRIPTION:
Bitter Creek Trib2 1.0
END DESCRIPTION:
XS GIS Cut Line= 3
        1426305.      6791187.97      1426294.81      6791287.55
        1426355.      6791587.98
#Sta/Elev= 30
  4899.9 2451.18  4902.4 2451.18  4940.1 2446.29  4947.1 2442.81  4952.1 2441.97
  4960.2 2438.33  4970.3 2433.18  4977.6 2430.36    4978 2429.86  4982.6 2429.86
    4983 2430.36  4990.4 2431.68  4997.7  2433.5  5010.7 2433.34  5041.3 2434.43
  5102.7 2437.63  5112.6 2438.47  5133.2 2439.35  5153.4 2441.53  5163.6 2442.17
  5173.8 2443.24  5184.1 2445.41  5194.2 2445.87  5204.4 2447.58    5230 2450.82
  5235.1 2451.01  5255.4    2453  5275.8 2454.26  5280.9 2455.65  5306.4 2457.37
#Mann= 4 ,-1 , 0
  4899.9     .16       0  4977.6     .07       0    4983     .16       0
  5102.7     .07       0
Bank Sta=4977.6,4983
XS Rating Curve= 0 ,0
Exp/Cntr=0.3,0.1

Type RM Length L Ch R = 1 ,448     ,362,362,362
BEGIN DESCRIPTION:
Bitter Creek Trib2 0.1
END DESCRIPTION:
XS GIS Cut Line= 3
      1426054.99      6791088.01      1425844.99      6791338.01
        1425855.      6791588.01
#Sta/Elev= 30
  4673.5 2449.69  4701.5 2447.86  4726.3 2445.46  4737.9 2443.93  4758.7 2436.35
    4773 2433.66  4787.3 2434.06  4822.4 2433.04  4869.9 2433.11  4908.3 2433.35
  4981.8 2431.42  4986.3 2430.75  4992.8 2430.79  4996.7 2429.67    5010 2428.88
  5027.3 2428.78  5027.7 2428.28  5032.3 2428.28  5032.8 2428.78    5050 2431.15
    5070 2432.78  5094.1 2436.78  5100.1 2437.82  5110.1 2438.46  5125.1 2440.86
  5150.1  2441.7  5165.3 2443.43  5192.3 2444.93  5210.2 2447.17  5250.2 2450.25
#Mann= 9 ,-1 , 0
  4673.5     .07       0  4726.3     .16       0  4869.9     .07       0
  4981.8     .16       0  5027.3     .07       0  5032.8     .16       0
  5094.1    .035       0  5165.3     .07       0  5192.3    .035       0
Bank Sta=5027.3,5032.8
XS Rating Curve= 0 ,0
Exp/Cntr=0.3,0.1

Type RM Length L Ch R = 1 ,86      ,0,0,0
BEGIN DESCRIPTION:
Bitter Creek Trib2 4291
END DESCRIPTION:
XS GIS Cut Line= 3
       1425964.4      6791101.73      1425555.28      6791174.25
      1425394.77       6791731.6
#Sta/Elev= 30
  4584.5 2437.96  4586.9 2437.85  4590.4 2435.95  4604.2 2434.44  4649.5 2432.27
  4898.7 2428.72  4929.2 2429.17  4959.7 2427.47    4994 2423.06  4994.5 2422.56
  5001.3 2423.06  5076.7 2431.19  5197.9 2431.24  5275.8 2431.17  5304.3 2434.45
  5343.2 2436.68  5348.4 2435.55  5376.9 2435.92  5382.1 2434.97  5409.9 2437.25
    5421 2435.83  5449.4 2438.09  5454.6 2437.43  5482.6  2440.8  5488.3 2442.81
  5493.5 2440.46  5503.4 2443.34  5513.8 2444.61  5546.9 2445.61    5580 2446.38
#Mann= 8 ,-1 , 0
  4584.5     .07       0  4586.9     .16       0    4994    .022       0
  5001.3    .022       0  5008.4     .07       0  5197.9    .035       0
  5409.9     .07       0  5546.9    .035       0
Bank Sta=4994,5001.3
XS Rating Curve= 0 ,0
Exp/Cntr=0.3,0.1

Chan Stop Cuts=-1
Use User Specified Reach Order=0
Composite Channel Slope=5