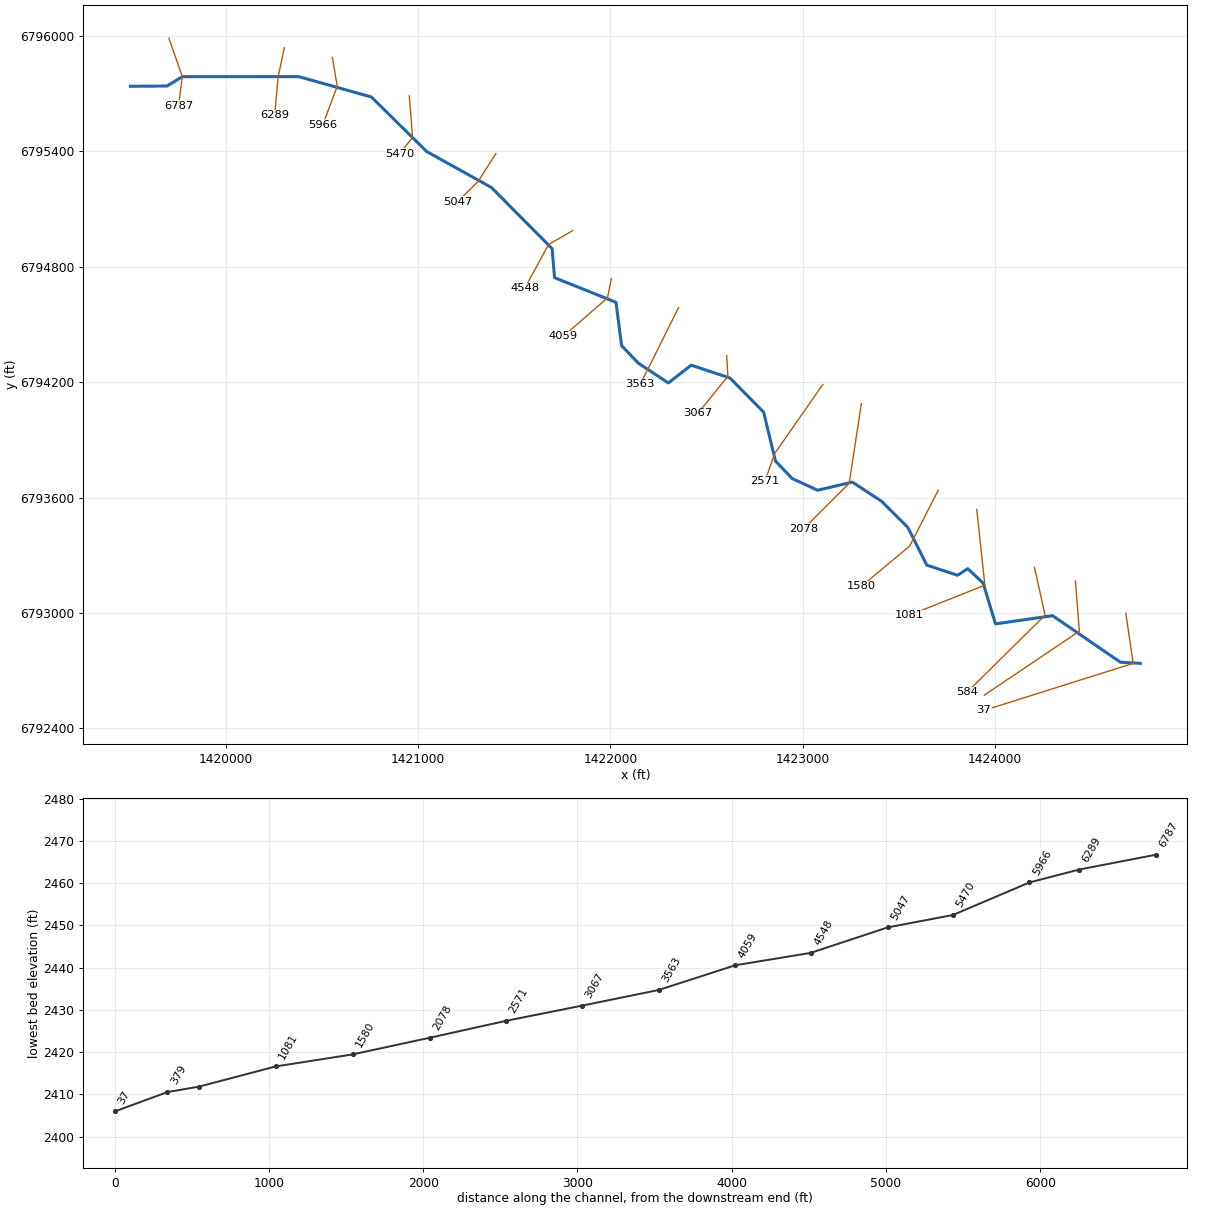
--- Bitter Creek Trib3.prj (project) ---

Proj Title=Bitter Creek Trib3 Base Level Engineering
Current Plan=p01
Default Exp/Contr=0.3,0.1
English Units
Geom File=g01
Flow File=f01
Plan File=p01
Y Axis Title=Elevation
X Axis Title(PF)=Main Channel Distance
X Axis Title(XS)=Station
BEGIN DESCRIPTION:
Bitter Creek Trib3
END DESCRIPTION:
DSS Export Rating Curves= 0
DSS Export Rating Curve Sorted= 0
DSS Export Volume Flow Curves= 0
DXF OffsetX= 0
DXF OffsetY= 0
DXF ScaleX= 1
DXF ScaleY= 10

--- Bitter Creek Trib3.p01 (plan) ---

Plan Title=Multiple Run
Short Identifier=Multiple
Geom File=g01
Flow File=f01
Subcritical Flow
K Sum by GR= 0
Std Step Tol= 0.01
Critical Tol= 0.01
Num of Std Step Trials= 20
Max Error Tol= 0.3
Flow Tol Ratio= 0.001
Split Flow NTrial= 30
Split Flow Tol= 0.02
Split Flow Ratio= 0.02
Log Output Level= 0
Friction Slope Method= 1
Unsteady Friction Slope Method= 2
Unsteady Bridges Friction Slope Method= 1
Parabolic Critical Depth
Global Vel Dist=  1 , 1 , 1
Global Log Level= 0
CheckData=True
Encroach Param= -1, 0, 0, 0
BEGIN DESCRIPTION:
Multiple Run
END DESCRIPTION:

--- Bitter Creek Trib3.f01 (steady flow) ---

Flow Title=Multiple
Number of Profiles=7
Profile Names=10-year,25-year,50-year,1pct_min,100-year,1pct_plu,500-year
River Rch & RM= Bitter Creek Tri,Reach-1,6787
     366     522     654     407     812    1620    1268
Boundary for River Rch & Prof#=Bitter Creek Tri,Reach-1,1
Up Type=0
Dn Type=3
Dn Slope=0.005
Boundary for River Rch & Prof#=Bitter Creek Tri,Reach-1,2
Up Type=0
Dn Type=3
Dn Slope=0.005
Boundary for River Rch & Prof#=Bitter Creek Tri,Reach-1,3
Up Type=0
Dn Type=3
Dn Slope=0.005
Boundary for River Rch & Prof#=Bitter Creek Tri,Reach-1,4
Up Type=0
Dn Type=3
Dn Slope=0.005
Boundary for River Rch & Prof#=Bitter Creek Tri,Reach-1,5
Up Type=0
Dn Type=3
Dn Slope=0.005
Boundary for River Rch & Prof#=Bitter Creek Tri,Reach-1,6
Up Type=0
Dn Type=3
Dn Slope=0.005
Boundary for River Rch & Prof#=Bitter Creek Tri,Reach-1,7
Up Type=0
Dn Type=3
Dn Slope=0.005

--- Bitter Creek Trib3.g01 (geometry) ---

Geom Title=Existing Conditions

River Reach=Bitter Creek Tri,Reach-1
Reach XY= 30
      1419505.00      6795738.00      1419695.34      6795739.37
      1419775.03      6795787.93      1420380.08      6795788.20
      1420757.43      6795682.48      1421045.32      6795398.78
      1421381.82      6795211.71      1421697.18      6794894.19
      1421710.04      6794743.08      1422029.36      6794614.99
      1422058.60      6794389.49      1422145.30      6794298.77
      1422301.67      6794195.61      1422420.34      6794288.04
      1422621.75      6794221.54      1422796.86      6794044.06
      1422858.54      6793789.46      1422945.29      6793698.75
      1423077.69      6793637.87      1423258.41      6793680.19
      1423411.05      6793579.84      1423547.14      6793444.17
      1423645.19      6793248.51      1423805.10      6793195.80
      1423858.35      6793230.01      1423938.57      6793154.83
      1424002.41      6792942.97      1424299.07      6792985.76
      1424652.50      6792743.35      1424755.00      6792738.00

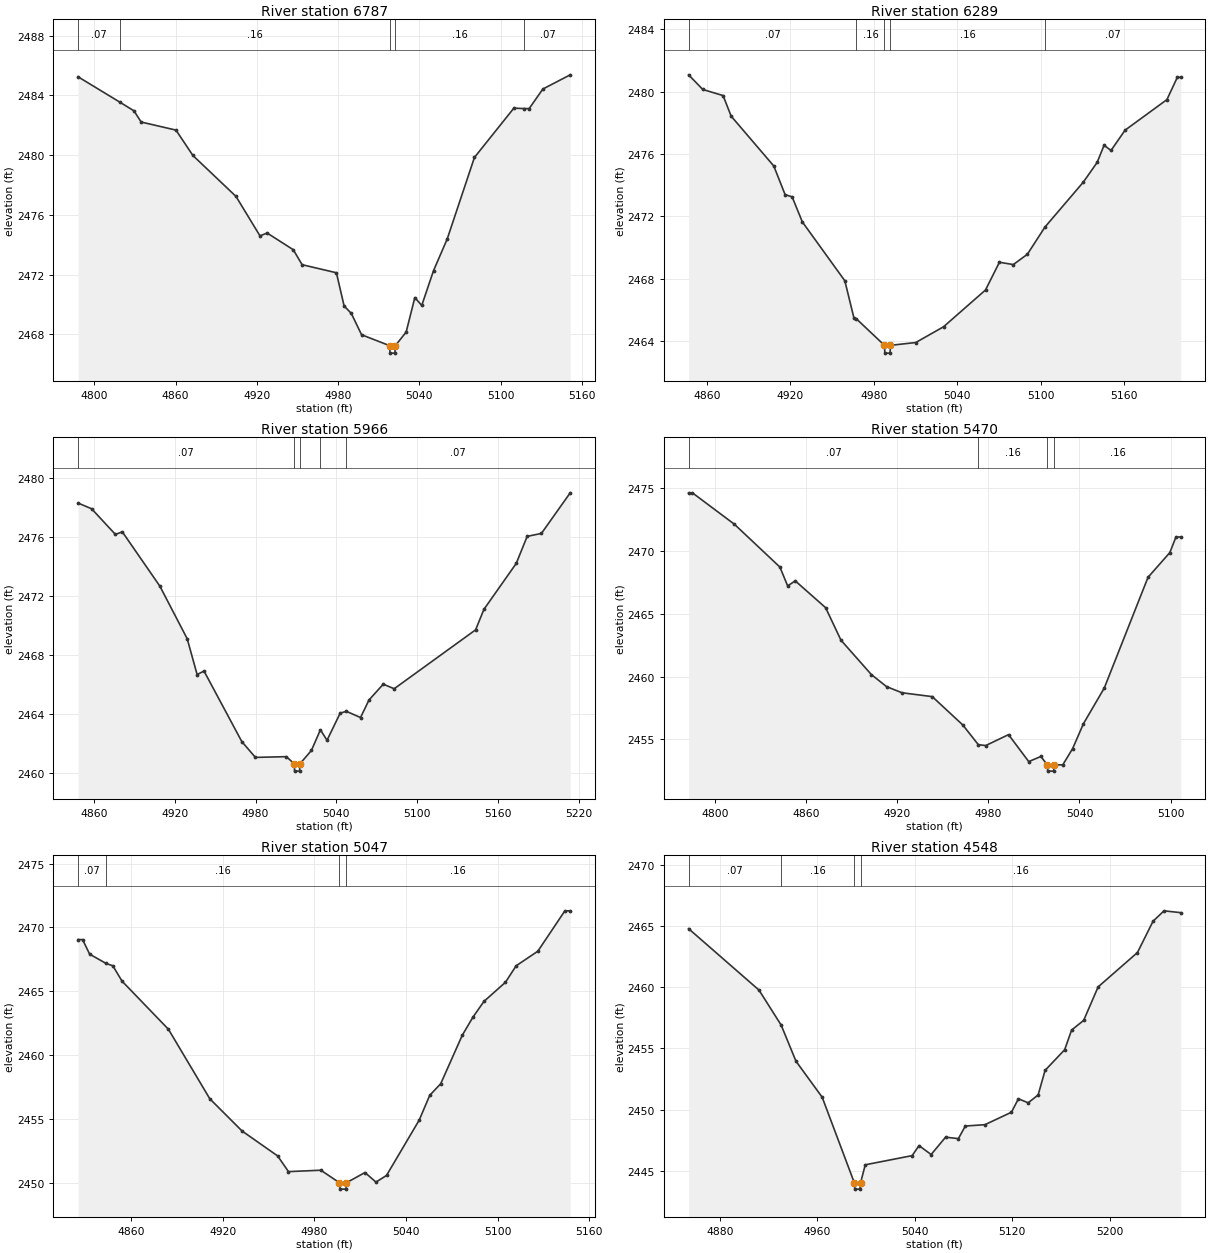
Type RM Length L Ch R = 1,6787,498,498,498
BEGIN DESCRIPTION:
Bitter Creek Trib3 13.0
END DESCRIPTION:
XS GIS Cut Line= 3
      1419704.99      6795988.02      1419775.03      6795787.93
      1419754.99      6795637.96
#Sta/Elev= 30
  4788.0 2485.24  4818.7 2483.55  4829.3 2482.96  4834.6 2482.21  4860.3 2481.67
  4872.8 2479.97  4904.6 2477.23  4922.3 2474.59  4927.6 2474.78  4946.9 2473.66
  4953.4 2472.66  4978.7 2472.12  4984.4 2469.90  4989.7 2469.40  4997.3 2467.97
  5018.0 2467.24  5018.3 2466.74  5021.9 2466.74  5022.2 2467.24  5030.2 2468.15
  5036.6 2470.46  5041.7 2469.93  5050.4 2472.26  5060.5 2474.38  5080.6 2479.84
  5109.7 2483.14  5117.5 2483.11  5121.0 2483.11  5131.1 2484.42  5151.3 2485.37
#Mann=5,-1,0
  4788.0    0.07       0  4818.7    0.16       0  5018.0    0.07       0
  5022.2    0.16       0  5117.5    0.07       0
Bank Sta=5018,5022.2
Exp/Cntr=0.3,0.1

Type RM Length L Ch R = 1,6289,323,323,323
BEGIN DESCRIPTION:
Bitter Creek Trib3 12.0
END DESCRIPTION:
XS GIS Cut Line= 3
      1420305.00      6795937.98      1420273.19      6795788.02
      1420255.00      6795588.04
#Sta/Elev= 30
  4846.7 2481.07  4856.9 2480.13  4871.5 2479.74  4877.3 2478.42  4908.0 2475.22
  4916.1 2473.39  4921.2 2473.24  4928.5 2471.64  4959.1 2467.86  4965.7 2465.45
  4967.4 2465.42  4987.6 2463.72  4987.9 2463.22  4991.6 2463.22  4991.9 2463.72
  5010.1 2463.90  5030.1 2464.91  5060.3 2467.27  5070.3 2469.05  5080.3 2468.90
  5090.4 2469.56  5103.1 2471.31  5130.6 2474.18  5140.6 2475.45  5145.6 2476.55
  5150.6 2476.22  5160.7 2477.52  5190.8 2479.48  5198.3 2480.91  5200.8 2480.91
#Mann=5,-1,0
  4846.7    0.07       0  4967.4    0.16       0  4987.6    0.07       0
  4991.9    0.16       0  5103.1    0.07       0
Bank Sta=4987.6,4991.9
Exp/Cntr=0.3,0.1

Type RM Length L Ch R = 1,5966,496,496,496
BEGIN DESCRIPTION:
Bitter Creek Trib3 11.0
END DESCRIPTION:
XS GIS Cut Line= 3
      1420555.00      6795887.99      1420580.07      6795738.18
      1420505.00      6795537.99
#Sta/Elev= 30
  4848.1 2478.32  4858.2 2477.93  4875.9 2476.19  4881.0 2476.37  4908.9 2472.69
  4929.2 2469.13  4936.6 2466.70  4941.7 2466.94  4969.8 2462.16  4979.9 2461.09
  5002.9 2461.14  5008.7 2460.66  5009.0 2460.16  5012.7 2460.16  5013.0 2460.66
  5021.5 2461.56  5028.2 2462.96  5033.1 2462.25  5042.9 2464.09  5047.5 2464.21
  5058.0 2463.79  5064.3 2464.98  5074.9 2466.05  5083.0 2465.74  5143.5 2469.73
  5149.7 2471.12  5173.7 2474.23  5181.8 2476.06  5192.4 2476.26  5213.8 2479.01
#Mann=5,-1,0
  4848.1    0.07       0  5008.7    0.07       0  5013.0    0.07       0
  5028.2    0.16       0  5047.5    0.07       0
Bank Sta=5008.7,5013
Exp/Cntr=0.3,0.1

Type RM Length L Ch R = 1,5470,423,423,423
BEGIN DESCRIPTION:
Bitter Creek Trib3 10.0
END DESCRIPTION:
XS GIS Cut Line= 3
      1420955.00      6795687.96      1420971.65      6795471.30
      1420904.99      6795387.99
#Sta/Elev= 30
  4782.7 2474.65  4785.2 2474.65  4812.8 2472.15  4842.8 2468.73  4847.9 2467.23
  4852.9 2467.63  4872.9 2465.49  4883.0 2462.90  4903.0 2460.16  4913.0 2459.20
  4923.1 2458.71  4943.1 2458.40  4963.2 2456.14  4973.4 2454.57  4978.3 2454.50
  4993.3 2455.37  5006.6 2453.22  5014.6 2453.63  5018.8 2452.96  5019.1 2452.46
  5023.0 2452.46  5023.3 2452.96  5029.0 2452.96  5035.5 2454.26  5042.6 2456.24
  5056.3 2459.08  5085.1 2467.91  5099.5 2469.89  5103.5 2471.13  5106.7 2471.13
#Mann=4,-1,0
  4782.7    0.07       0  4973.4    0.16       0  5018.8    0.07       0
  5023.3    0.16       0
Bank Sta=5018.8,5023.3
Exp/Cntr=0.3,0.1

Type RM Length L Ch R = 1,5047,499,499,499
BEGIN DESCRIPTION:
Bitter Creek Trib3 9.0
END DESCRIPTION:
XS GIS Cut Line= 3
      1421405.01      6795388.01      1421310.72      6795240.83
      1421204.98      6795137.98
#Sta/Elev= 30
  4825.2 2469.05  4828.2 2469.05  4832.8 2467.91  4843.6 2467.18  4848.0 2467.00
  4854.0 2465.80  4884.4 2462.03  4911.5 2456.59  4932.6 2454.07  4955.9 2452.12
  4963.0 2450.89  4984.2 2451.00  4996.4 2450.02  4996.8 2449.52  5000.7 2449.52
  5001.0 2450.02  5013.1 2450.82  5020.3 2450.07  5027.2 2450.59  5048.6 2454.92
  5055.5 2456.86  5062.7 2457.77  5076.8 2461.56  5083.8 2462.98  5091.0 2464.21
  5105.1 2465.71  5112.1 2467.00  5126.3 2468.14  5144.0 2471.30  5147.5 2471.30
#Mann=4,-1,0
  4825.2    0.07       0  4843.6    0.16       0  4996.4    0.07       0
  5001.0    0.16       0
Bank Sta=4996.4,5001
Exp/Cntr=0.3,0.1

Type RM Length L Ch R = 1,4548,489,489,489
BEGIN DESCRIPTION:
Bitter Creek Trib3 8.0
END DESCRIPTION:
XS GIS Cut Line= 3
      1421804.98      6794987.99      1421678.83      6794914.87
      1421554.98      6794687.97
#Sta/Elev= 30
  4854.2 2464.79  4912.0 2459.77  4930.2 2456.91  4942.4 2453.95  4963.9 2451.01
  4990.4 2443.99  4990.7 2443.49  4995.0 2443.49  4995.4 2443.99  4999.3 2445.48
  5037.8 2446.23  5043.5 2447.05  5053.4 2446.32  5065.3 2447.74  5075.8 2447.62
  5081.5 2448.65  5097.6 2448.76  5119.4 2449.78  5125.1 2450.88  5133.1 2450.55
  5141.3 2451.19  5147.0 2453.20  5163.1 2454.89  5168.8 2456.50  5178.7 2457.29
  5190.6 2460.03  5222.9 2462.84  5235.7 2465.40  5244.7 2466.25  5258.5 2466.10
#Mann=4,-1,0
  4854.2    0.07       0  4930.2    0.16       0  4990.4    0.07       0
  4995.4    0.16       0
Bank Sta=4990.4,4995.4
Exp/Cntr=0.3,0.1

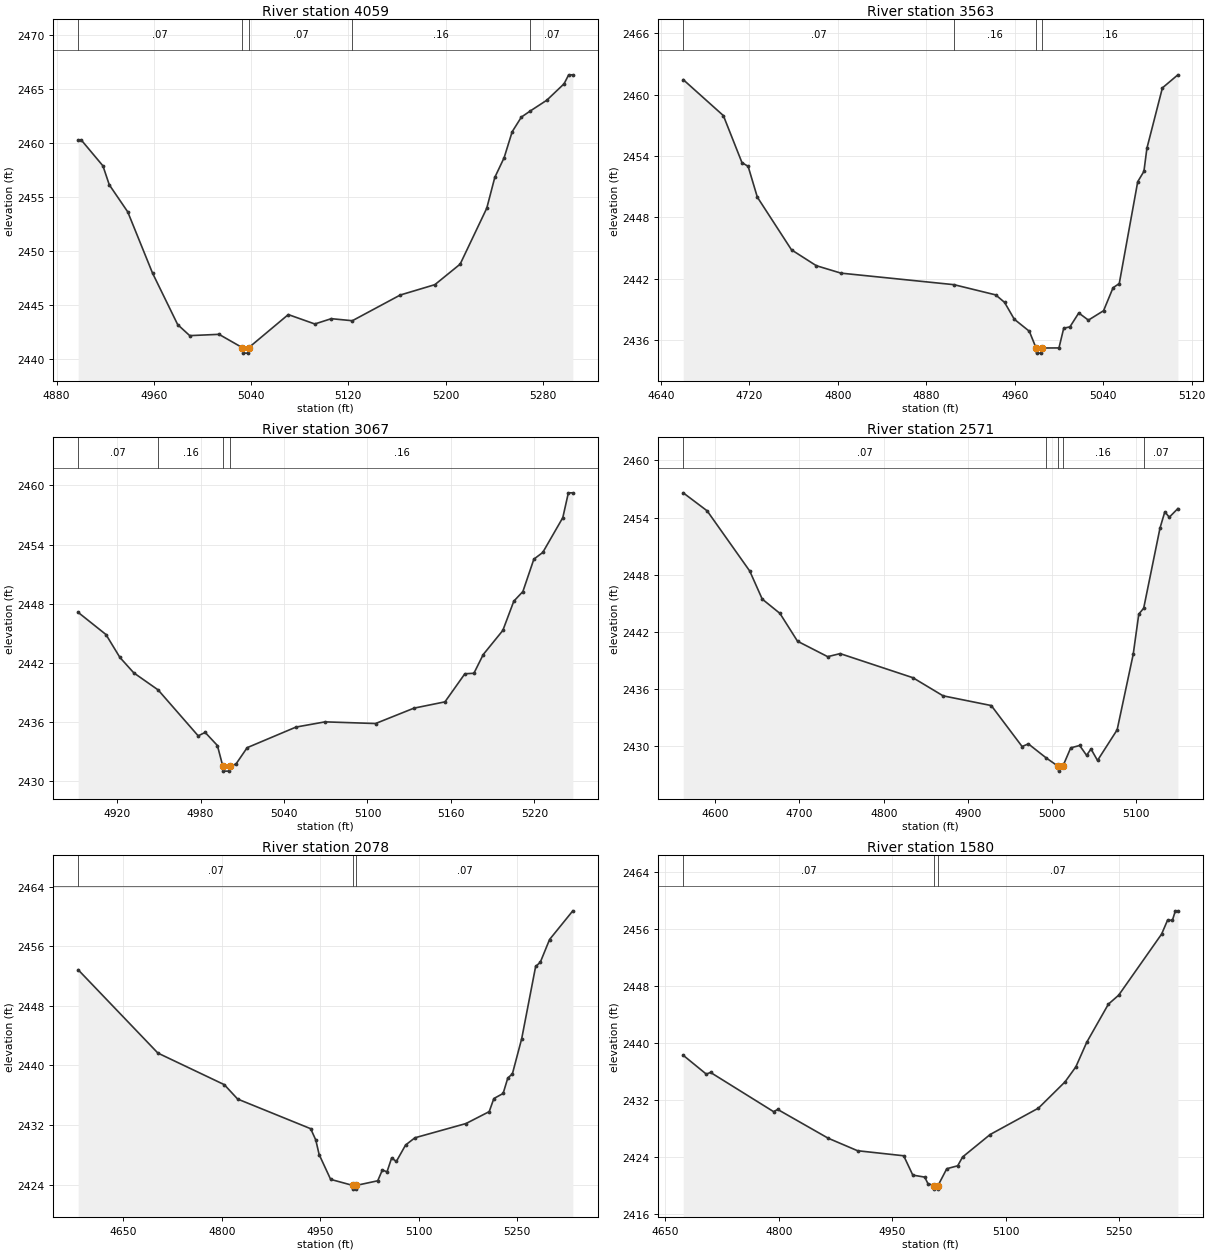
Type RM Length L Ch R = 1,4059,496,496,496
BEGIN DESCRIPTION:
Bitter Creek Trib3 7.0
END DESCRIPTION:
XS GIS Cut Line= 3
      1422005.00      6794738.02      1421985.09      6794637.68
      1421754.96      6794437.97
#Sta/Elev= 30
  4897.7 2460.29  4900.3 2460.29  4918.1 2457.90  4923.3 2456.15  4938.5 2453.64
  4958.9 2447.97  4979.6 2443.20  4989.5 2442.18  5013.6 2442.30  5032.9 2441.06
  5033.3 2440.56  5037.6 2440.56  5038.0 2441.06  5070.6 2444.13  5092.4 2443.26
  5106.0 2443.75  5123.3 2443.56  5162.7 2445.94  5191.2 2446.90  5212.0 2448.80
  5233.9 2453.98  5240.5 2456.83  5248.2 2458.66  5254.8 2461.06  5262.4 2462.42
  5269.8 2462.99  5283.3 2463.98  5297.5 2465.50  5301.3 2466.33  5304.7 2466.33
#Mann=5,-1,0
  4897.7    0.07       0  5032.9    0.07       0  5038.0    0.07       0
  5123.3    0.16       0  5269.8    0.07       0
Bank Sta=5032.9,5038
Exp/Cntr=0.3,0.1

Type RM Length L Ch R = 1,3563,496,496,496
BEGIN DESCRIPTION:
Bitter Creek Trib3 6.0
END DESCRIPTION:
XS GIS Cut Line= 3
      1422354.99      6794587.98      1422203.35      6794284.00
      1422155.00      6794187.99
#Sta/Elev= 30
  4660.3 2461.48  4696.6 2457.96  4713.4 2453.36  4719.0 2452.99  4727.3 2449.98
  4758.2 2444.82  4780.6 2443.27  4802.9 2442.54  4905.1 2441.41  4942.8 2440.41
  4950.8 2439.68  4959.6 2438.03  4973.2 2436.85  4979.3 2435.21  4979.7 2434.71
  4984.1 2434.71  4984.5 2435.21  5000.0 2435.22  5004.3 2437.15  5009.9 2437.28
  5017.9 2438.64  5026.6 2437.94  5040.3 2438.86  5048.9 2441.11  5054.5 2441.52
  5071.2 2451.49  5076.8 2452.50  5079.5 2454.76  5093.5 2460.67  5107.5 2461.95
#Mann=4,-1,0
  4660.3    0.07       0  4905.1    0.16       0  4979.3    0.07       0
  4984.5    0.16       0
Bank Sta=4979.3,4984.5
Exp/Cntr=0.3,0.1

Type RM Length L Ch R = 1,3067,496,496,496
BEGIN DESCRIPTION:
Bitter Creek Trib3 5.0
END DESCRIPTION:
XS GIS Cut Line= 3
      1422605.00      6794337.96      1422611.17      6794230.14
      1422455.00      6794038.00
#Sta/Elev= 30
  4892.0 2447.12  4912.0 2444.87  4922.0 2442.55  4932.0 2440.98  4949.5 2439.25
  4978.3 2434.59  4983.3 2434.94  4992.1 2433.61  4996.0 2431.51  4996.4 2431.01
  5000.8 2431.01  5001.2 2431.51  5005.5 2431.74  5013.5 2433.39  5048.6 2435.48
  5069.5 2436.01  5105.8 2435.84  5133.4 2437.40  5155.7 2438.04  5170.0 2440.89
  5176.5 2440.94  5183.2 2442.84  5197.3 2445.29  5205.2 2448.26  5211.7 2449.23
  5219.6 2452.52  5226.0 2453.20  5240.4 2456.73  5244.4 2459.25  5247.6 2459.25
#Mann=4,-1,0
  4892.0    0.07       0  4949.5    0.16       0  4996.0    0.07       0
  5001.2    0.16       0
Bank Sta=4996,5001.2
Exp/Cntr=0.3,0.1

Type RM Length L Ch R = 1,2571,493,493,493
BEGIN DESCRIPTION:
Bitter Creek Trib3 4.0
END DESCRIPTION:
XS GIS Cut Line= 3
      1423105.03      6794188.04      1422854.55      6793828.72
      1422805.00      6793687.99
#Sta/Elev= 30
  4562.0 2456.59  4590.4 2454.70  4641.0 2448.38  4655.8 2445.44  4676.8 2443.94
  4697.7 2441.02  4733.5 2439.40  4748.3 2439.72  4834.7 2437.19  4870.5 2435.29
  4927.7 2434.27  4964.3 2429.97  4971.7 2430.25  4993.1 2428.76  5007.2 2427.89
  5007.6 2427.39  5012.6 2427.89  5022.0 2429.83  5032.6 2430.08  5040.8 2429.05
  5046.1 2429.71  5053.8 2428.51  5077.1 2431.72  5096.2 2439.66  5102.8 2443.87
  5108.6 2444.48  5128.0 2452.90  5133.7 2454.60  5139.0 2454.03  5149.2 2454.94
#Mann=5,-1,0
  4562.0    0.07       0  4993.1    0.16       0  5007.2    0.07       0
  5012.6    0.16       0  5108.6    0.07       0
Bank Sta=5007.2,5012.6
Exp/Cntr=0.3,0.1

Type RM Length L Ch R = 1,2078,498,498,498
BEGIN DESCRIPTION:
Bitter Creek Trib3 3.0
END DESCRIPTION:
XS GIS Cut Line= 3
      1423305.00      6794087.97      1423241.84      6793674.16
      1423004.98      6793437.98
#Sta/Elev= 30
  4581.4 2452.84  4702.8 2441.66  4803.9 2437.42  4824.2 2435.49  4935.4 2431.51
  4943.2 2429.99  4948.3 2428.04  4965.8 2424.71  4999.4 2423.90  4999.9 2423.40
  5004.4 2423.40  5004.8 2423.90  5037.5 2424.52  5044.6 2425.98  5051.6 2425.71
  5058.7 2427.59  5065.8 2427.11  5079.9 2429.32  5094.1 2430.29  5171.8 2432.20
  5207.2 2433.80  5214.3 2435.56  5228.4 2436.24  5235.5 2438.31  5242.5 2438.87
  5256.7 2443.60  5277.9 2453.28  5285.0 2453.85  5299.1 2456.90  5334.5 2460.75
#Mann=3,-1,0
  4581.4    0.07       0  4999.4    0.07       0  5004.8    0.07       0
Bank Sta=4999.4,5004.8
Exp/Cntr=0.3,0.1

Type RM Length L Ch R = 1,1580,499,499,499
BEGIN DESCRIPTION:
Bitter Creek Trib3 2.0
END DESCRIPTION:
XS GIS Cut Line= 3
      1423704.99      6793637.98      1423556.31      6793347.63
      1423304.97      6793137.98
#Sta/Elev= 30
  4673.8 2438.29  4704.3 2435.64  4709.9 2435.88  4793.1 2430.37  4798.7 2430.67
  4865.3 2426.63  4904.1 2424.87  4965.1 2424.16  4977.1 2421.44  4992.9 2421.16
  4997.0 2420.26  5005.0 2419.97  5005.4 2419.47  5010.0 2419.47  5010.4 2419.97
  5022.0 2422.34  5036.4 2422.75  5042.9 2423.99  5079.3 2427.15  5143.1 2430.86
  5178.2 2434.55  5192.5 2436.66  5206.9 2440.12  5235.5 2445.48  5249.1 2446.74
  5305.8 2455.33  5313.6 2457.27  5320.1 2457.28  5324.0 2458.60  5327.3 2458.60
#Mann=3,-1,0
  4673.8    0.07       0  5005.0    0.07       0  5010.4    0.07       0
Bank Sta=5005,5010.4
Exp/Cntr=0.3,0.1

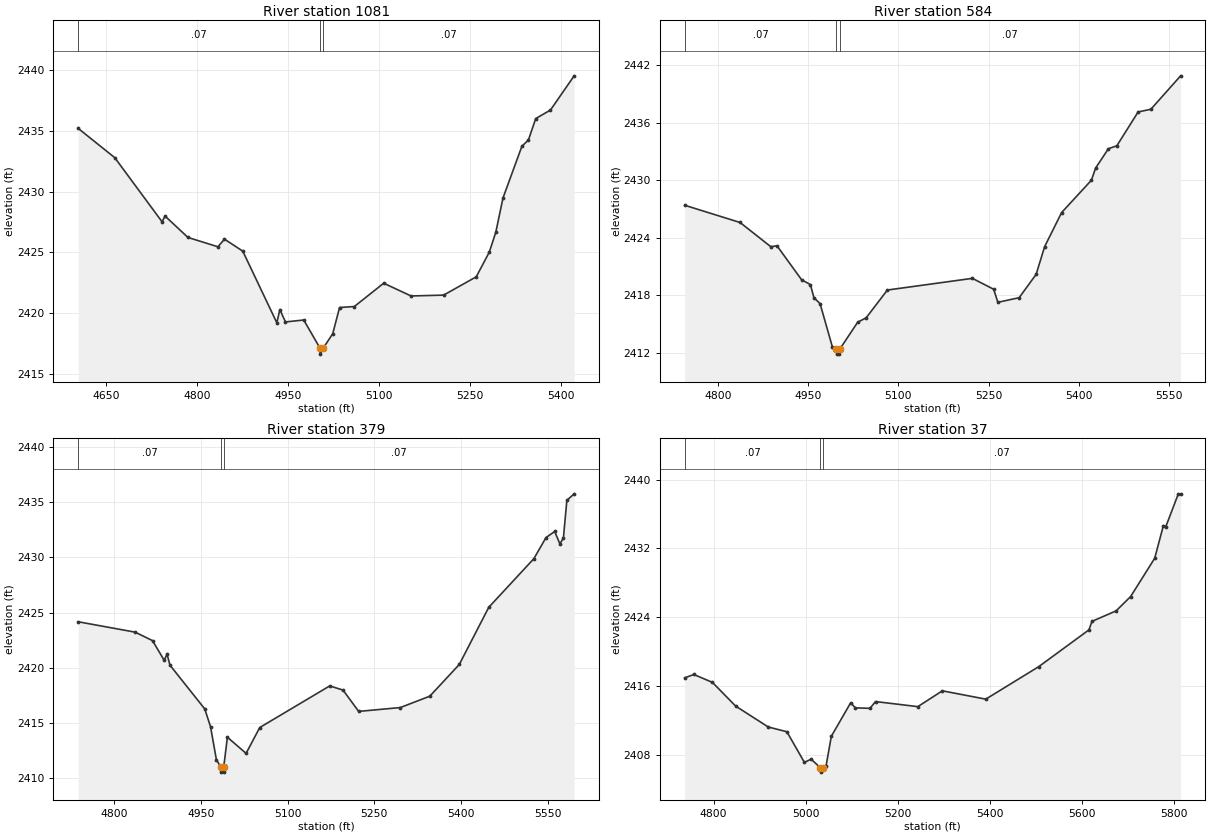
Type RM Length L Ch R = 1,1081,497,497,497
BEGIN DESCRIPTION:
Bitter Creek Trib3 1.0
END DESCRIPTION:
XS GIS Cut Line= 3
      1423905.00      6793537.97      1423947.18      6793144.23
      1423554.96      6792987.98
#Sta/Elev= 30
  4604.0 2435.21  4664.3 2432.80  4742.3 2427.52  4747.3 2427.99  4785.0 2426.23
  4834.5 2425.46  4845.3 2426.09  4875.5 2425.10  4931.7 2419.20  4936.7 2420.29
  4945.9 2419.27  4976.1 2419.43  5002.8 2417.12  5003.2 2416.62  5008.3 2417.12
  5023.9 2418.30  5035.2 2420.46  5059.5 2420.54  5108.0 2422.46  5153.1 2421.41
  5206.9 2421.48  5260.7 2422.99  5282.2 2425.02  5293.0 2426.67  5304.8 2429.48
  5336.0 2433.74  5346.8 2434.26  5358.8 2436.02  5383.1 2436.72  5422.2 2439.54
#Mann=3,-1,0
  4604.0    0.07       0  5002.8    0.07       0  5008.3    0.07       0
Bank Sta=5002.8,5008.3
Exp/Cntr=0.3,0.1

Type RM Length L Ch R = 1,584,205,205,205
BEGIN DESCRIPTION:
Bitter Creek Trib3 0.1
END DESCRIPTION:
XS GIS Cut Line= 3
      1424205.00      6793238.02      1424260.18      6792988.45
      1423854.98      6792587.98
#Sta/Elev= 30
  4744.4 2427.38  4836.6 2425.58  4887.8 2423.05  4898.0 2423.15  4939.0 2419.60
  4953.6 2419.10  4959.5 2417.73  4969.7 2417.11  4990.2 2412.59  4996.8 2412.34
  4997.3 2411.84  5001.9 2411.84  5002.3 2412.34  5032.3 2415.17  5046.4 2415.63
  5081.7 2418.53  5223.2 2419.75  5258.6 2418.61  5265.6 2417.25  5301.0 2417.73
  5329.3 2420.17  5343.4 2423.06  5371.7 2426.62  5421.2 2429.99  5428.3 2431.27
  5449.5 2433.28  5463.6 2433.59  5499.0 2437.12  5520.2 2437.40  5569.7 2440.89
#Mann=3,-1,0
  4744.4    0.07       0  4996.8    0.07       0  5002.3    0.07       0
Bank Sta=4996.8,5002.3
Exp/Cntr=0.3,0.1

Type RM Length L Ch R = 1,379,342,342,342
BEGIN DESCRIPTION:
Bitter Creek Trib3 4292
END DESCRIPTION:
XS GIS Cut Line= 3
      1424417.99      6793166.13      1424438.48      6792905.03
      1423944.48      6792572.67
#Sta/Elev= 30
  4738.1 2424.17  4836.5 2423.23  4866.6 2422.46  4886.6 2420.69  4891.7 2421.23
  4896.7 2420.24  4956.9 2416.27  4966.9 2414.65  4977.0 2411.67  4984.2 2411.05
  4984.7 2410.55  4989.3 2410.55  4989.7 2411.05  4996.0 2413.71  5028.3 2412.25
  5051.9 2414.59  5172.9 2418.36  5195.9 2417.98  5222.9 2416.05  5294.9 2416.40
  5345.9 2417.43  5396.8 2420.30  5447.8 2425.48  5525.8 2429.89  5546.8 2431.80
  5561.8 2432.35  5570.7 2431.23  5576.8 2431.75  5582.8 2435.17  5595.4 2435.76
#Mann=3,-1,0
  4738.1    0.07       0  4984.2    0.07       0  4989.7    0.07       0
Bank Sta=4984.2,4989.7
Exp/Cntr=0.3,0.1

Type RM Length L Ch R = 1,37,0,0,0
BEGIN DESCRIPTION:
Bitter Creek Trib3 4293
END DESCRIPTION:
XS GIS Cut Line= 3
      1424680.14      6792997.68      1424718.13      6792737.54
      1423941.29      6792492.74
#Sta/Elev= 30
  4737.1 2416.93  4757.0 2417.32  4797.4 2416.40  4847.9 2413.64  4918.7 2411.21
  4959.1 2410.66  4997.2 2407.09  5011.8 2407.47  5032.0 2406.46  5032.4 2405.96
  5037.5 2406.46  5044.2 2406.67  5055.7 2410.13  5097.6 2414.02  5108.1 2413.44
  5139.6 2413.38  5151.7 2414.17  5243.6 2413.58  5296.9 2415.42  5391.2 2414.45
  5506.5 2418.24  5615.3 2422.51  5621.9 2423.50  5674.3 2424.72  5705.8 2426.38
  5758.2 2430.84  5777.1 2434.65  5782.4 2434.53  5809.5 2438.33  5814.5 2438.34
#Mann=3,-1,0
  4737.1    0.07       0  5032.0    0.07       0  5037.5    0.07       0
Bank Sta=5032,5037.5
Exp/Cntr=0.3,0.1

Chan Stop Cuts=-1