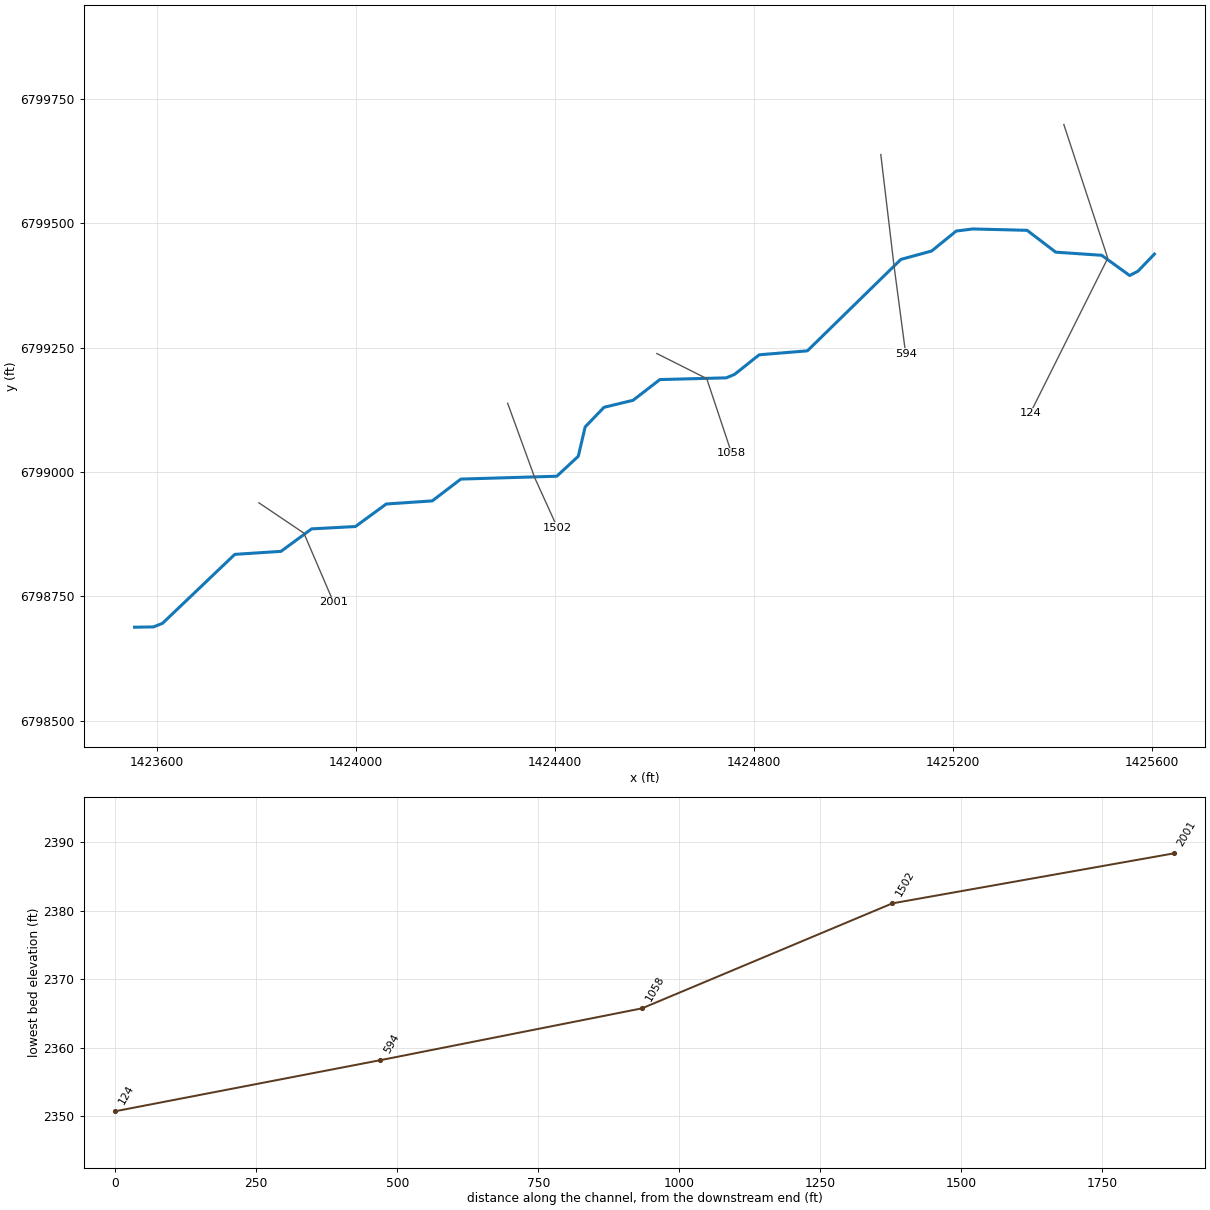
--- Bitter Creek Trib4.prj (project) ---

Proj Title=Bitter Creek Trib4 Base Level Engineering
Current Plan=p01
Default Exp/Contr=0.3,0.1
English Units
Geom File=g01
Flow File=f01
Plan File=p01
Y Axis Title=Elevation
X Axis Title(PF)=Main Channel Distance
X Axis Title(XS)=Station
BEGIN DESCRIPTION:
Bitter Creek Trib4
END DESCRIPTION:
DSS Export Rating Curves= 0
DSS Export Rating Curve Sorted= 0
DSS Export Volume Flow Curves= 0
DXF OffsetX= 0
DXF OffsetY= 0
DXF ScaleX= 1
DXF ScaleY= 10

--- Bitter Creek Trib4.p01 (plan) ---

Plan Title=Multiple Run
Short Identifier=Multiple
Geom File=g01
Flow File=f01
Subcritical Flow
K Sum by GR= 0
Std Step Tol= 0.01
Critical Tol= 0.01
Num of Std Step Trials= 20
Max Error Tol= 0.3
Flow Tol Ratio= 0.001
Split Flow NTrial= 30
Split Flow Tol= 0.02
Split Flow Ratio= 0.02
Log Output Level= 0
Friction Slope Method= 1
Unsteady Friction Slope Method= 2
Unsteady Bridges Friction Slope Method= 1
Parabolic Critical Depth
Global Vel Dist=  1 , 1 , 1
Global Log Level= 0
CheckData=True
Encroach Param= -1, 0, 0, 0
BEGIN DESCRIPTION:
Multiple Run
END DESCRIPTION:

--- Bitter Creek Trib4.f01 (steady flow) ---

Flow Title=Multiple
Program Version=4.10
Number of Profiles= 7
Profile Names=10-year,25-year,50-year,1pct_min,100-year,1pct_plu,500-year
River Rch & RM=Bitter Creek Tri,Reach-1         ,2001
     374     538     678     426     850    1695    1348
Boundary for River Rch & Prof#=Bitter Creek Tri,Reach-1         , 1
Up Type= 0
Dn Type= 3
Dn Slope=0.016
Boundary for River Rch & Prof#=Bitter Creek Tri,Reach-1         , 2
Up Type= 0
Dn Type= 3
Dn Slope=0.016
Boundary for River Rch & Prof#=Bitter Creek Tri,Reach-1         , 3
Up Type= 0
Dn Type= 3
Dn Slope=0.016
Boundary for River Rch & Prof#=Bitter Creek Tri,Reach-1         , 4
Up Type= 0
Dn Type= 3
Dn Slope=0.016
Boundary for River Rch & Prof#=Bitter Creek Tri,Reach-1         , 5
Up Type= 0
Dn Type= 3
Dn Slope=0.016
Boundary for River Rch & Prof#=Bitter Creek Tri,Reach-1         , 6
Up Type= 0
Dn Type= 3
Dn Slope=0.016
Boundary for River Rch & Prof#=Bitter Creek Tri,Reach-1         , 7
Up Type= 0
Dn Type= 3
Dn Slope=0.016
DSS Import GetInterval= 0
DSS Import GetPeak= 0
DSS Import FillOption= 0

--- Bitter Creek Trib4.g01 (geometry) ---

Geom Title=Existing Conditions
Program Version=4.10

River Reach=Bitter Creek Tri,Reach-1
Reach XY= 30
        1423555.        6798688.      1423593.16      6798688.59
      1423611.21      6798695.76       1423756.5      6798834.39
      1423849.43      6798840.47      1423910.97      6798885.65
      1423999.03      6798890.35      1424060.97      6798935.65
       1424153.4      6798941.86      1424210.94      6798985.74
      1424403.75      6798991.45      1424446.97      6799031.64
      1424460.76      6799090.51      1424498.66      6799129.98
      1424557.15      6799144.15      1424610.93      6799185.75
      1424744.49      6799189.23      1424761.06      6799196.14
      1424810.57      6799235.53      1424907.43      6799243.52
      1425095.32      6799427.24      1425157.17      6799444.14
      1425206.56      6799484.26      1425239.84      6799488.48
      1425349.06      6799485.75       1425406.6      6799441.85
      1425499.12      6799435.54      1425555.14       6799394.9
      1425571.84      6799403.54        1425605.        6799438.

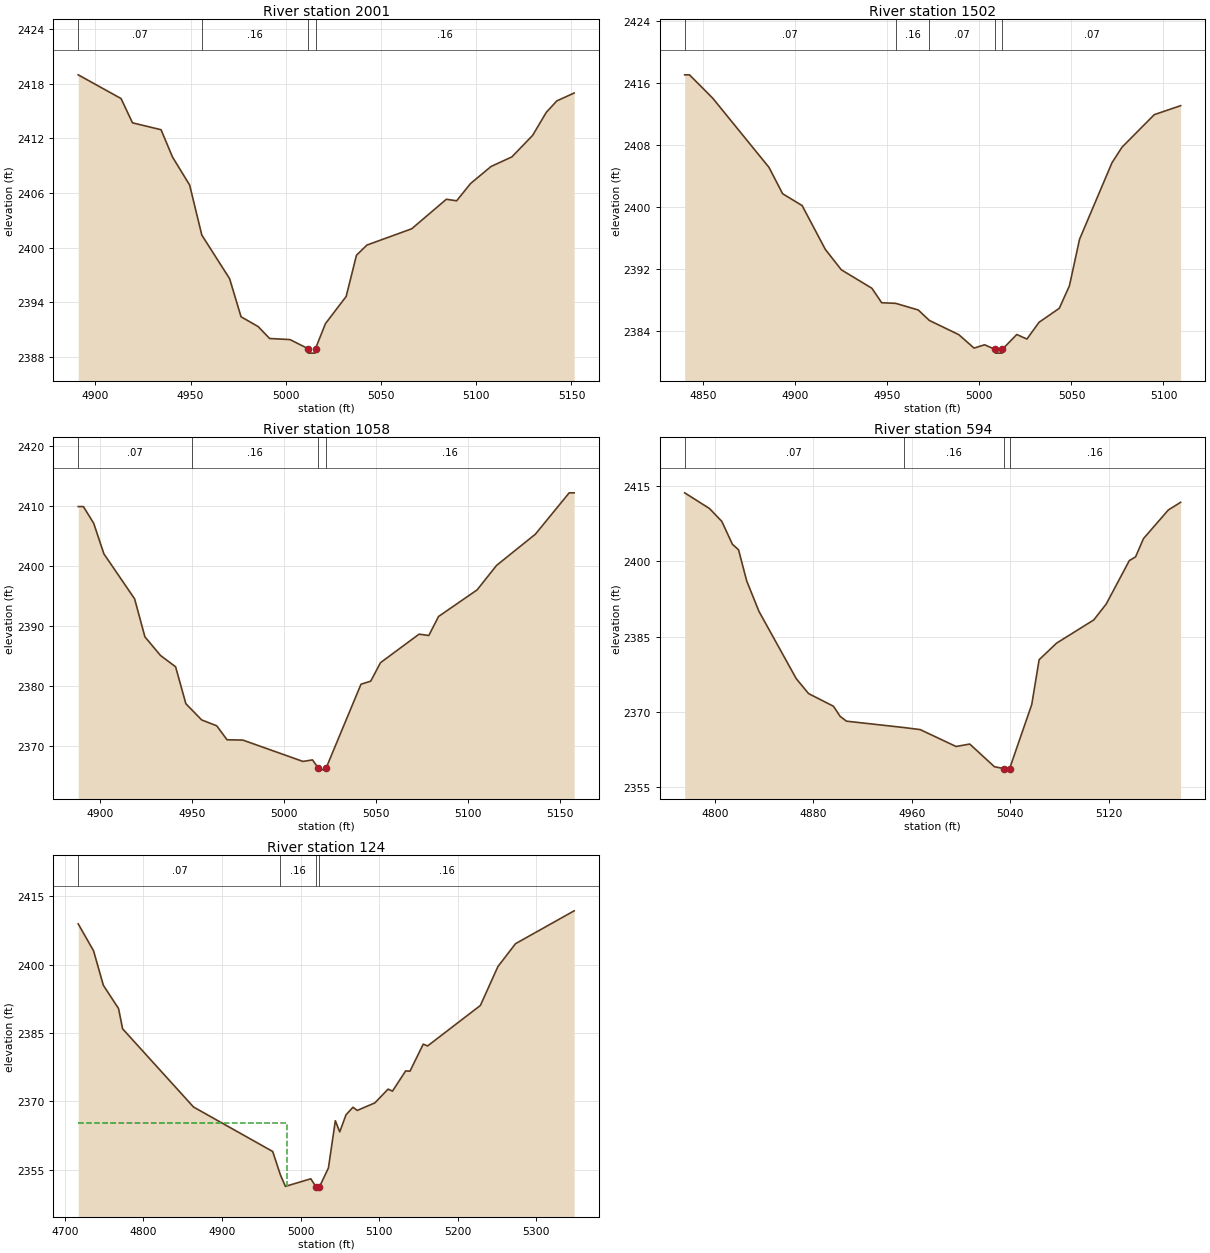
Type RM Length L Ch R = 1 ,2001    ,499,499,499
BEGIN DESCRIPTION:
Bitter Creek Trib4 3.0
END DESCRIPTION:
XS GIS Cut Line= 3
      1423804.97      6798938.02      1423895.37      6798877.11
      1423955.02      6798737.96
#Sta/Elev= 30
    4891    2419  4913.5 2416.39  4919.5 2413.72  4934.5 2412.96  4940.5 2409.96
  4949.5 2406.88  4955.9 2401.37  4970.5 2396.57  4976.5 2392.38  4985.5  2391.3
  4991.5 2389.99  5002.2 2389.87  5011.6 2388.88  5011.8 2388.38  5015.3 2388.38
  5015.6 2388.88  5020.8 2391.62  5031.7 2394.62  5037.1 2399.15  5042.6 2400.27
  5066.1 2402.06  5084.3 2405.31  5089.7 2405.14    5097 2407.04  5107.8 2408.92
  5118.7 2409.97  5129.6 2412.34  5136.8 2414.88  5142.3 2416.13  5151.4    2417
#Mann= 4 ,-1 , 0
    4891     .07       0  4955.9     .16       0  5011.6     .07       0
  5015.6     .16       0
Bank Sta=5011.6,5015.6
XS Rating Curve= 0 ,0
Exp/Cntr=0.3,0.1

Type RM Length L Ch R = 1 ,1502    ,444,444,444
BEGIN DESCRIPTION:
Bitter Creek Trib4 2.0
END DESCRIPTION:
XS GIS Cut Line= 3
      1424305.01      6799137.96      1424359.78      6798987.52
        1424405.      6798888.01
#Sta/Elev= 30
  4839.9 2417.08  4842.5 2417.08  4855.1 2414.07  4885.7 2405.11  4893.1  2401.7
  4903.7 2400.17  4916.3  2394.5    4925 2391.86  4941.6 2389.47  4946.9  2387.6
  4954.5 2387.52  4966.8 2386.66  4972.8 2385.31  4988.8 2383.47  4997.1 2381.73
  5002.8 2382.16  5008.4 2381.58  5008.7 2381.08  5012.3 2381.08  5012.5 2381.58
  5020.3 2383.49  5025.8  2382.9  5032.4 2385.07  5043.4 2386.88  5048.9 2389.79
  5054.4 2395.81    5072  2405.7  5077.5 2407.73    5095 2411.93  5109.3 2413.09
#Mann= 5 ,-1 , 0
  4839.9     .07       0  4954.5     .16       0  4972.8     .07       0
  5008.4     .07       0  5012.5     .07       0
Bank Sta=5008.4,5012.5
XS Rating Curve= 0 ,0
Exp/Cntr=0.3,0.1

Type RM Length L Ch R = 1 ,1058    ,464,464,464
BEGIN DESCRIPTION:
Bitter Creek Trib4 1.0
END DESCRIPTION:
XS GIS Cut Line= 3
      1424604.98      6799238.01      1424705.14      6799187.67
      1424755.01      6799037.96
#Sta/Elev= 30
  4887.9 2409.88  4890.7 2409.88  4896.3 2407.11  4901.9 2401.98  4918.6 2394.48
  4924.2 2388.15  4932.7 2385.03  4940.9 2383.15  4946.5 2376.98  4949.7 2375.98
  4955.1 2374.28  4963.3  2373.3  4968.9 2370.97  4977.5 2370.92  5010.2 2367.36
  5015.4 2367.61  5018.6 2366.24  5018.9 2365.74  5022.8 2366.24  5041.8 2380.24
  5047.1 2380.75  5052.4 2383.83  5073.4 2388.59  5078.7 2388.37    5084 2391.54
    5105 2395.98  5115.6 2400.07  5136.7 2405.27  5155.1 2412.17  5157.8 2412.17
#Mann= 4 ,-1 , 0
  4887.9     .07       0  4949.7     .16       0  5018.6     .07       0
  5022.8     .16       0
Bank Sta=5018.6,5022.8
XS Rating Curve= 0 ,0
Exp/Cntr=0.3,0.1

Type RM Length L Ch R = 1 ,594     ,470,470,470
BEGIN DESCRIPTION:
Bitter Creek Trib4 0.1
END DESCRIPTION:
XS GIS Cut Line= 3
        1425055.      6799638.02      1425081.53      6799414.99
      1425104.99      6799238.04
#Sta/Elev= 30
  4775.4 2413.65  4795.6 2410.52  4805.6 2407.95  4814.2  2403.4  4819.2 2402.29
  4825.8  2396.1  4835.8 2390.01  4866.1  2376.6  4876.1 2373.63  4896.3 2371.11
  4901.8 2369.08  4906.9 2368.13  4953.5 2366.86  4966.8 2366.45    4996 2363.08
  5007.1 2363.57  5027.2 2359.04  5035.2 2358.67  5035.5 2358.17  5039.5 2358.67
  5057.5 2371.45  5063.5 2380.38  5077.7 2383.69  5107.9 2388.31    5118 2391.47
  5136.8 2400.14  5141.9 2400.89  5148.3 2404.52  5168.5 2410.23  5178.5 2411.76
#Mann= 4 ,-1 , 0
  4775.4     .07       0  4953.5     .16       0  5035.2     .07       0
  5039.5     .16       0
Bank Sta=5035.2,5039.5
XS Rating Curve= 0 ,0
Exp/Cntr=0.3,0.1

Type RM Length L Ch R = 1 ,124     ,0,0,0
BEGIN DESCRIPTION:
Bitter Creek Trib4 4294
END DESCRIPTION:
XS GIS Cut Line= 3
      1425422.92      6799698.43       1425511.2      6799429.66
      1425355.56       6799118.4
#Sta/Elev= 30
  4717.1 2408.98  4736.6 2403.08  4749.1 2395.49  4768.4 2390.39  4773.6 2385.93
  4863.8 2368.75  4964.5 2358.98  4974.4  2353.8  4980.7 2351.32    5013 2352.98
  5019.6 2351.21  5019.9 2350.71    5024 2351.21  5035.4 2355.36  5044.2 2365.74
  5049.8 2363.29  5057.8 2367.04  5066.6  2368.7  5072.1    2368  5094.5 2369.66
  5111.3 2372.68  5116.9 2372.24  5133.6 2376.67  5139.2 2376.63    5156 2382.56
  5161.6 2382.17  5228.7 2391.06    5251  2399.6  5273.4 2404.63    5348 2411.85
#Mann= 4 ,-1 , 0
  4717.1     .07       0  4974.4     .16       0  5019.6     .07       0
    5024     .16       0
#XS Ineff= 2 , 0
         4982.84 2365.27
Permanent Ineff=
       F       F
Bank Sta=5019.6,5024
XS Rating Curve= 0 ,0
Exp/Cntr=0.3,0.1

Chan Stop Cuts=-1
Use User Specified Reach Order=0
Composite Channel Slope=5