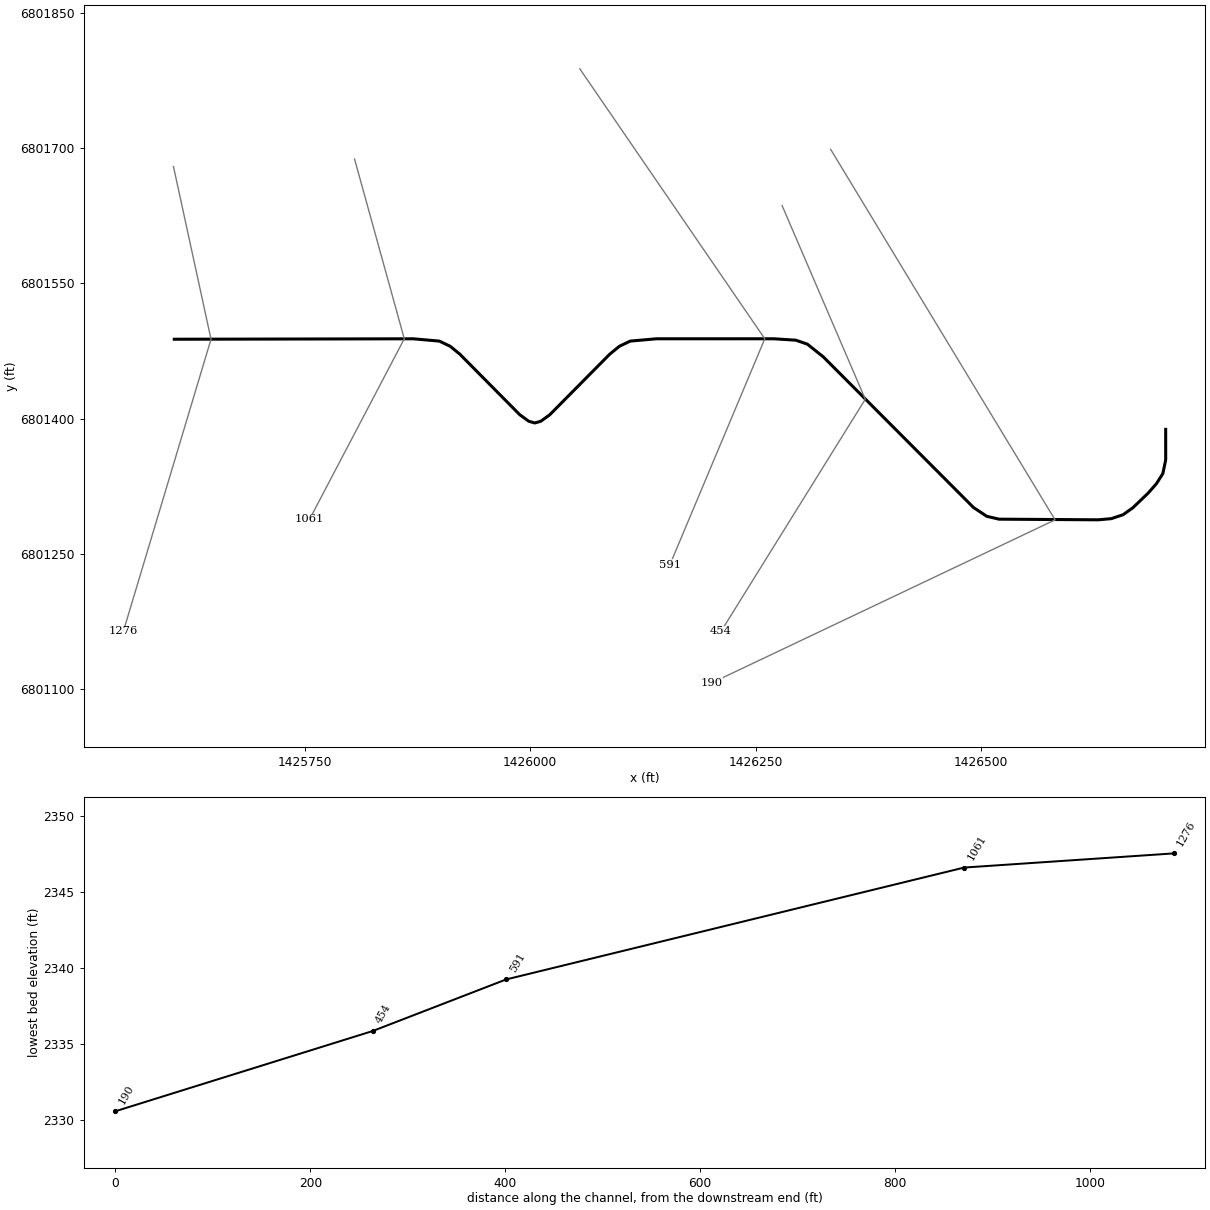
--- Bitter Creek Trib5.prj (project) ---

Proj Title=Bitter Creek Trib5 Base Level Engineering
Current Plan=p01
Default Exp/Contr=0.3,0.1
English Units
Geom File=g01
Flow File=f01
Plan File=p01
Y Axis Title=Elevation
X Axis Title(PF)=Main Channel Distance
X Axis Title(XS)=Station
BEGIN DESCRIPTION:
Bitter Creek Trib5
END DESCRIPTION:
DSS Export Rating Curves= 0
DSS Export Rating Curve Sorted= 0
DSS Export Volume Flow Curves= 0
DXF OffsetX= 0
DXF OffsetY= 0
DXF ScaleX= 1
DXF ScaleY= 10

--- Bitter Creek Trib5.p01 (plan) ---

Plan Title=Multiple Run
Short Identifier=Multiple
Geom File=g01
Flow File=f01
Subcritical Flow
K Sum by GR= 0
Std Step Tol= 0.01
Critical Tol= 0.01
Num of Std Step Trials= 20
Max Error Tol= 0.3
Flow Tol Ratio= 0.001
Split Flow NTrial= 30
Split Flow Tol= 0.02
Split Flow Ratio= 0.02
Log Output Level= 0
Friction Slope Method= 1
Unsteady Friction Slope Method= 2
Unsteady Bridges Friction Slope Method= 1
Parabolic Critical Depth
Global Vel Dist=  1 , 1 , 1
Global Log Level= 0
CheckData=True
Encroach Param= -1, 0, 0, 0
BEGIN DESCRIPTION:
Multiple Run
END DESCRIPTION:

--- Bitter Creek Trib5.f01 (steady flow) ---

Flow Title=Multiple
Number of Profiles=7
Profile Names=10-year,25-year,50-year,1pct_min,100-year,1pct_plu,500-year
River Rch & RM= Bitter Creek Tri,Reach-1,1276
     319     458     577     362     722    1440    1145
Boundary for River Rch & Prof#=Bitter Creek Tri,Reach-1,1
Up Type=0
Dn Type=3
Dn Slope=0.005
Boundary for River Rch & Prof#=Bitter Creek Tri,Reach-1,2
Up Type=0
Dn Type=3
Dn Slope=0.005
Boundary for River Rch & Prof#=Bitter Creek Tri,Reach-1,3
Up Type=0
Dn Type=3
Dn Slope=0.005
Boundary for River Rch & Prof#=Bitter Creek Tri,Reach-1,4
Up Type=0
Dn Type=3
Dn Slope=0.005
Boundary for River Rch & Prof#=Bitter Creek Tri,Reach-1,5
Up Type=0
Dn Type=3
Dn Slope=0.005
Boundary for River Rch & Prof#=Bitter Creek Tri,Reach-1,6
Up Type=0
Dn Type=3
Dn Slope=0.005
Boundary for River Rch & Prof#=Bitter Creek Tri,Reach-1,7
Up Type=0
Dn Type=3
Dn Slope=0.005

--- Bitter Creek Trib5.g01 (geometry) ---

Geom Title=Existing Conditions

River Reach=Bitter Creek Tri,Reach-1
Reach XY= 30
      1425605.00      6801488.00      1425870.20      6801488.49
      1425899.15      6801485.92      1425911.19      6801480.15
      1425921.76      6801471.50      1425988.35      6801404.23
      1425998.34      6801396.98      1426005.00      6801395.10
      1426011.66      6801396.98      1426021.65      6801404.23
      1426088.24      6801471.50      1426098.81      6801480.15
      1426110.85      6801485.93      1426139.80      6801488.49
      1426270.20      6801488.50      1426294.57      6801486.95
      1426307.45      6801482.54      1426325.16      6801468.40
      1426491.68      6801301.37      1426506.47      6801291.53
      1426520.16      6801288.36      1426630.18      6801287.65
      1426644.69      6801288.94      1426657.69      6801293.26
      1426668.66      6801301.08      1426685.50      6801317.22
      1426694.71      6801327.67      1426701.88      6801338.98
      1426705.02      6801354.16      1426705.00      6801388.00

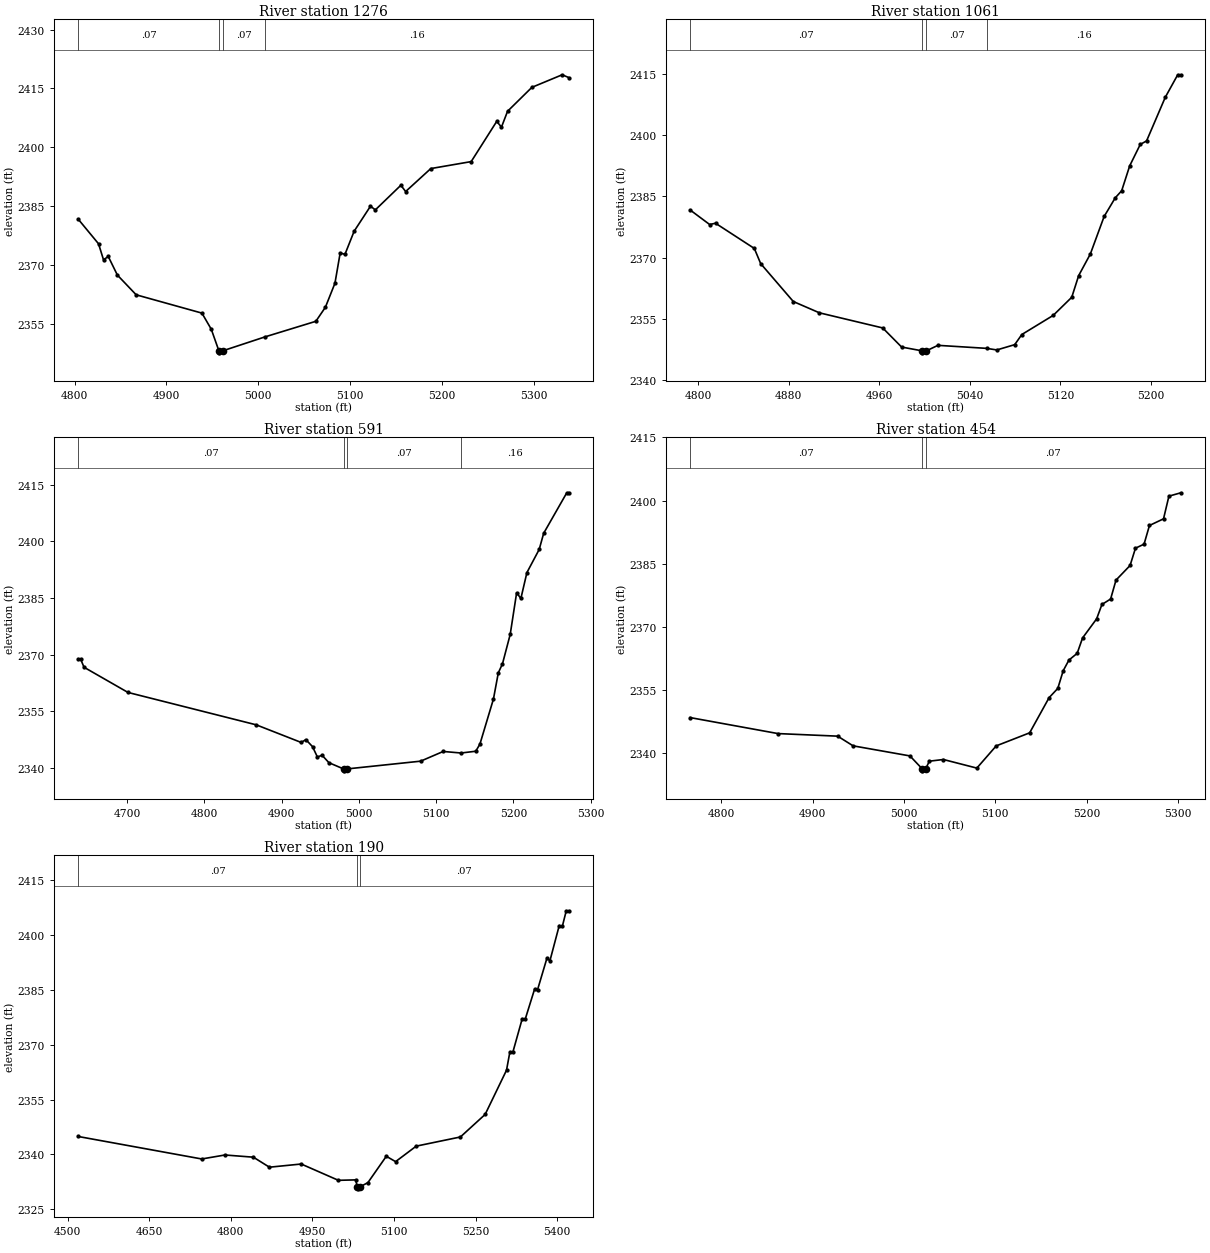
Type RM Length L Ch R = 1,1276,215,215,215
BEGIN DESCRIPTION:
Bitter Creek Trib5 4297
END DESCRIPTION:
XS GIS Cut Line= 3
      1425604.09      6801679.63      1425645.76      6801488.01
      1425548.53      6801163.98
#Sta/Elev= 30
  4803.9 2381.63  4826.0 2375.36  4831.4 2371.28  4836.6 2372.12  4846.5 2367.38
  4867.0 2362.34  4938.6 2357.67  4948.8 2353.55  4957.1 2348.03  4957.3 2347.53
  4961.1 2348.03  5007.4 2351.61  5062.7 2355.58  5073.1 2359.17  5083.5 2365.30
  5089.2 2373.03  5094.4 2372.67  5104.4 2378.57  5122.2 2384.96  5127.5 2384.02
  5155.3 2390.30  5160.5 2388.70  5187.9 2394.56  5231.9 2396.34  5259.7 2406.60
  5264.9 2405.15  5271.5 2409.18  5298.0 2415.29  5331.0 2418.50  5338.3 2417.78
#Mann=4,-1,0
  4803.9    0.07       0  4957.1    0.07       0  4961.1    0.07       0
  5007.4    0.16       0
Bank Sta=4957.1,4961.1
Exp/Cntr=0.3,0.1

Type RM Length L Ch R = 1,1061,470,470,470
BEGIN DESCRIPTION:
Bitter Creek Trib5 1.0
END DESCRIPTION:
XS GIS Cut Line= 3
      1425805.00      6801687.98      1425860.20      6801488.48
      1425755.00      6801288.00
#Sta/Elev= 30
  4793.0 2381.64  4810.1 2378.10  4815.3 2378.41  4849.6 2372.22  4855.2 2368.50
  4884.0 2359.20  4907.1 2356.42  4963.0 2352.71  4979.7 2348.02  4997.6 2347.10
  4997.9 2346.60  5001.6 2347.10  5011.8 2348.44  5054.8 2347.70  5063.8 2347.31
  5079.6 2348.61  5085.9 2351.10  5113.6 2355.79  5130.0 2360.24  5136.1 2365.56
  5146.4 2370.85  5158.6 2380.07  5168.4 2384.64  5174.1 2386.39  5181.2 2392.51
  5190.5 2397.75  5196.1 2398.62  5212.6 2409.32  5223.6 2414.85  5226.4 2414.85
#Mann=4,-1,0
  4793.0    0.07       0  4997.6    0.07       0  5001.6    0.07       0
  5054.8    0.16       0
Bank Sta=4997.6,5001.6
Exp/Cntr=0.3,0.1

Type RM Length L Ch R = 1,591,137,137,137
BEGIN DESCRIPTION:
Bitter Creek Trib5 0.1
END DESCRIPTION:
XS GIS Cut Line= 3
      1426054.98      6801788.03      1426260.20      6801488.49
      1426154.99      6801237.98
#Sta/Elev= 30
  4636.9 2368.79  4640.0 2368.79  4644.4 2366.67  4701.2 2360.01  4867.2 2351.43
  4925.3 2346.77  4931.4 2347.51  4940.0 2345.66  4946.3 2342.92  4952.4 2343.38
  4961.2 2341.41  4980.2 2339.75  4980.4 2339.25  4984.2 2339.75  5079.9 2341.81
  5109.1 2344.38  5132.2 2343.97  5151.2 2344.44  5156.6 2346.32  5174.1 2358.26
  5180.4 2365.20  5185.8 2367.59  5195.8 2375.38  5204.1 2386.40  5209.6 2384.88
  5217.4 2391.74  5233.3 2397.87  5239.1 2402.15  5269.0 2412.87  5271.7 2412.87
#Mann=4,-1,0
  4636.9    0.07       0  4980.2    0.07       0  4984.2    0.07       0
  5132.2    0.16       0
Bank Sta=4980.2,4984.2
Exp/Cntr=0.3,0.1

Type RM Length L Ch R = 1,454,264,264,264
BEGIN DESCRIPTION:
Bitter Creek Trib5 4296
END DESCRIPTION:
XS GIS Cut Line= 3
      1426279.42      6801636.25      1426371.71      6801421.43
      1426211.73      6801163.99
#Sta/Elev= 30
  4766.2 2348.49  4862.2 2344.70  4927.5 2344.09  4944.4 2341.79  5006.6 2339.40
  5019.9 2336.36  5020.2 2335.86  5023.9 2336.36  5027.8 2338.15  5043.2 2338.55
  5079.8 2336.51  5101.0 2341.78  5137.6 2344.88  5158.9 2353.23  5168.4 2355.42
  5174.3 2359.61  5180.6 2362.15  5189.6 2363.74  5195.5 2367.39  5210.9 2371.93
  5216.7 2375.34  5226.2 2376.63  5232.1 2381.12  5247.5 2384.59  5253.4 2388.69
  5262.8 2389.65  5268.7 2394.08  5284.1 2395.66  5290.0 2401.04  5303.1 2401.84
#Mann=3,-1,0
  4766.2    0.07       0  5019.9    0.07       0  5023.9    0.07       0
Bank Sta=5019.9,5023.9
Exp/Cntr=0.3,0.1

Type RM Length L Ch R = 1,190,0,0,0
BEGIN DESCRIPTION:
Bitter Creek Trib5 4295
END DESCRIPTION:
XS GIS Cut Line= 3
      1426333.24      6801698.73      1426582.29      6801287.58
      1426201.35      6801106.71
#Sta/Elev= 30
  4519.3 2344.91  4746.4 2338.76  4789.1 2339.85  4841.4 2339.25  4870.9 2336.51
  4929.4 2337.38  4997.8 2332.92  5029.3 2333.04  5032.9 2331.09  5033.1 2330.59
  5036.9 2331.09  5052.1 2332.30  5085.9 2339.50  5103.0 2338.03  5140.9 2342.27
  5222.2 2344.78  5267.7 2350.95  5307.0 2363.04  5313.1 2367.97  5318.7 2368.00
  5335.9 2377.13  5341.4 2377.00  5358.6 2385.21  5364.1 2385.06  5381.3 2393.67
  5386.9 2393.01  5404.0 2402.63  5409.6 2402.37  5416.9 2406.66  5421.7 2406.66
#Mann=3,-1,0
  4519.3    0.07       0  5032.9    0.07       0  5036.9    0.07       0
Bank Sta=5032.9,5036.9
Exp/Cntr=0.3,0.1

Chan Stop Cuts=-1