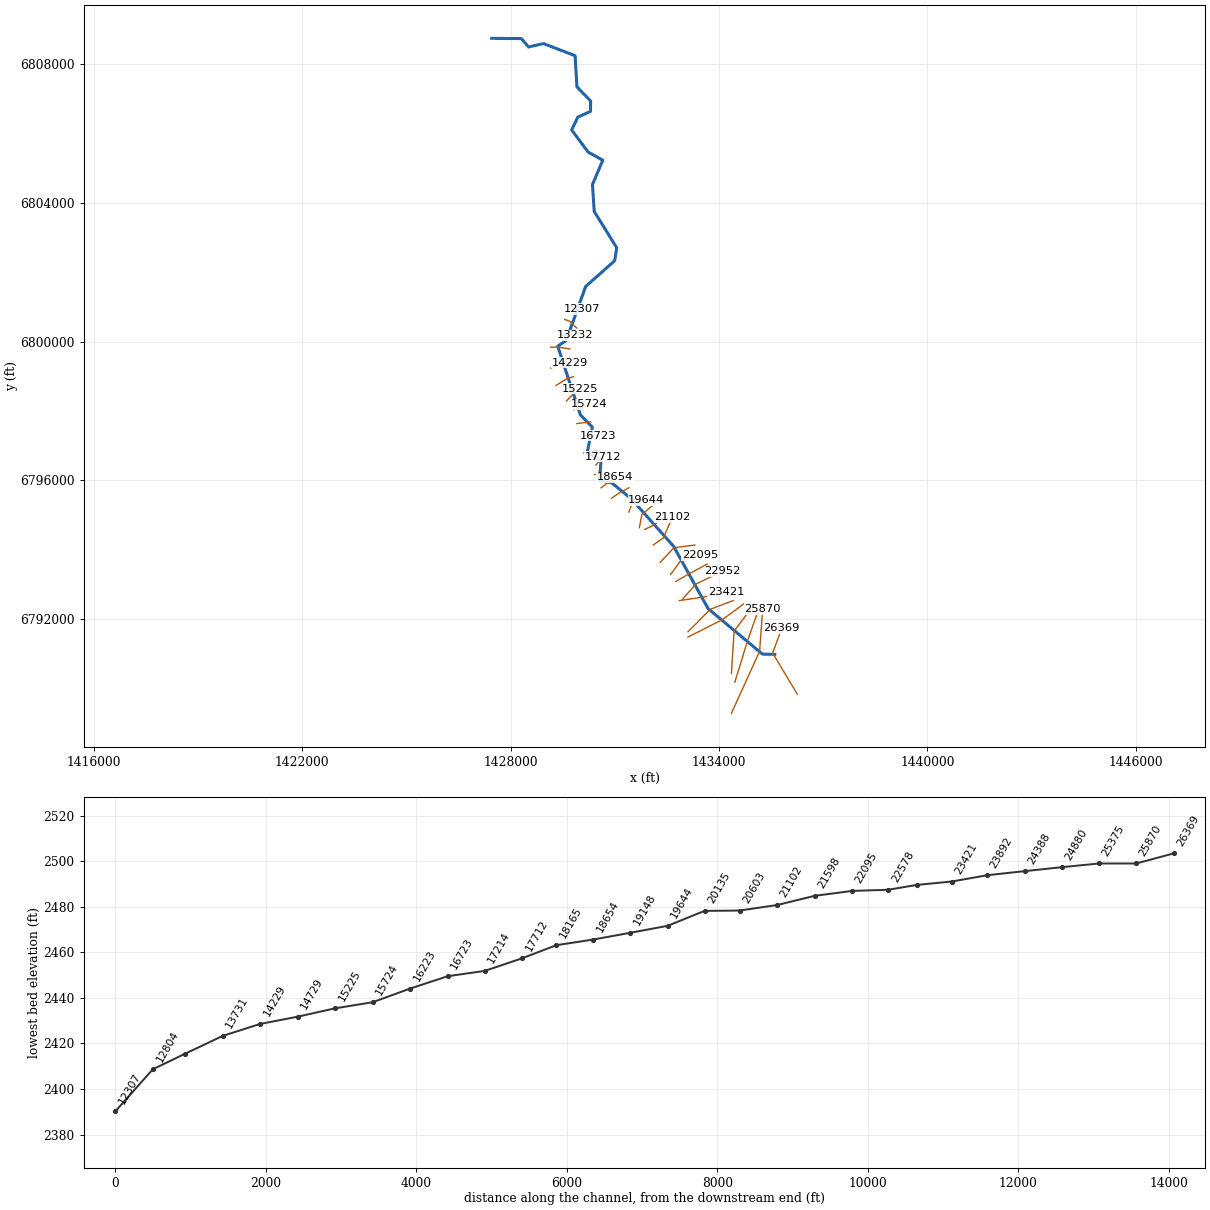
--- Bitter Creek Trib6.prj (project) ---

Proj Title=Bitter Creek Trib6 Base Level Engineering
Current Plan=p01
Default Exp/Contr=0.3,0.1
English Units
Geom File=g01
Flow File=f01
Plan File=p01
Y Axis Title=Elevation
X Axis Title(PF)=Main Channel Distance
X Axis Title(XS)=Station
BEGIN DESCRIPTION:
Bitter Creek Trib6
END DESCRIPTION:
DSS Export Rating Curves= 0
DSS Export Rating Curve Sorted= 0
DSS Export Volume Flow Curves= 0
DXF OffsetX= 0
DXF OffsetY= 0
DXF ScaleX= 1
DXF ScaleY= 10

--- Bitter Creek Trib6.p01 (plan) ---

Plan Title=Multiple Run
Short Identifier=Multiple
Geom File=g01
Flow File=f01
Subcritical Flow
K Sum by GR= 0
Std Step Tol= 0.01
Critical Tol= 0.01
Num of Std Step Trials= 20
Max Error Tol= 0.3
Flow Tol Ratio= 0.001
Split Flow NTrial= 30
Split Flow Tol= 0.02
Split Flow Ratio= 0.02
Log Output Level= 0
Friction Slope Method= 1
Unsteady Friction Slope Method= 2
Unsteady Bridges Friction Slope Method= 1
Parabolic Critical Depth
Global Vel Dist=  1 , 1 , 1
Global Log Level= 0
CheckData=True
Encroach Param= -1, 0, 0, 0
BEGIN DESCRIPTION:
Multiple Run
END DESCRIPTION:

--- Bitter Creek Trib6.f01 (steady flow) ---

Flow Title=Multiple
Program Version=4.10
Number of Profiles= 7
Profile Names=10-year,25-year,50-year,1pct_min,100-year,1pct_plu,500-year
River Rch & RM=Bitter Creek Tri,Reach-1         ,26369
      70      85      95      53     105     209     129
River Rch & RM=Bitter Creek Tri,Reach-1         ,25870
     169     222     262     154     307     612     425
River Rch & RM=Bitter Creek Tri,Reach-1         ,21102
     551     789     989     615    1227    2449    1913
River Rch & RM=Bitter Creek Tri,Reach-1         ,10327
    1127    1684    2175    1392    2777    5540    4583
River Rch & RM=Bitter Creek Tri,Reach-1         ,5436
    1287    1935    2512    1614    3220    6425    6361
River Rch & RM=Bitter Creek Tri,Reach-1         ,2391
    1571    2385    3117    2015    4020    8022    6778
Boundary for River Rch & Prof#=Bitter Creek Tri,Reach-1         , 1
Up Type= 0
Dn Type= 3
Dn Slope=0.005
Boundary for River Rch & Prof#=Bitter Creek Tri,Reach-1         , 2
Up Type= 0
Dn Type= 3
Dn Slope=0.005
Boundary for River Rch & Prof#=Bitter Creek Tri,Reach-1         , 3
Up Type= 0
Dn Type= 3
Dn Slope=0.005
Boundary for River Rch & Prof#=Bitter Creek Tri,Reach-1         , 4
Up Type= 0
Dn Type= 3
Dn Slope=0.005
Boundary for River Rch & Prof#=Bitter Creek Tri,Reach-1         , 5
Up Type= 0
Dn Type= 3
Dn Slope=0.005
Boundary for River Rch & Prof#=Bitter Creek Tri,Reach-1         , 6
Up Type= 0
Dn Type= 3
Dn Slope=0.005
Boundary for River Rch & Prof#=Bitter Creek Tri,Reach-1         , 7
Up Type= 0
Dn Type= 3
Dn Slope=0.005
DSS Import GetInterval= 0
DSS Import GetPeak= 0
DSS Import FillOption= 0

--- Bitter Creek Trib6.g01 (geometry) ---

Geom Title=Existing Conditions
Program Version=4.10

River Reach=Bitter Creek Tri,Reach-1
Reach XY= 30
        1435605.        6790988.      1435248.93      6790996.15
      1433684.45      6792307.45      1432691.87      6794101.21
      1431472.05      6795471.51       1430907.7      6795932.65
      1430558.45      6795989.25      1430601.64      6796586.75
      1430205.38      6796803.15      1430353.11      6797532.29
      1430008.46      6797889.25      1429354.45      6799863.13
      1429601.47      6800039.45      1430160.83       6801590.3
      1430994.49      6802328.21      1431054.91      6802703.39
      1430405.93      6803748.48      1430356.08      6804527.46
      1430653.39      6805226.17      1430231.42      6805460.85
       1429755.6      6806098.63      1429934.46      6806468.54
      1430297.47      6806631.56      1430303.02       6806932.1
      1429908.43      6807339.22        1429855.        6808238.
      1428945.35      6808586.64        1428517.      6808489.16
      1428308.31      6808729.98        1427455.        6808738.

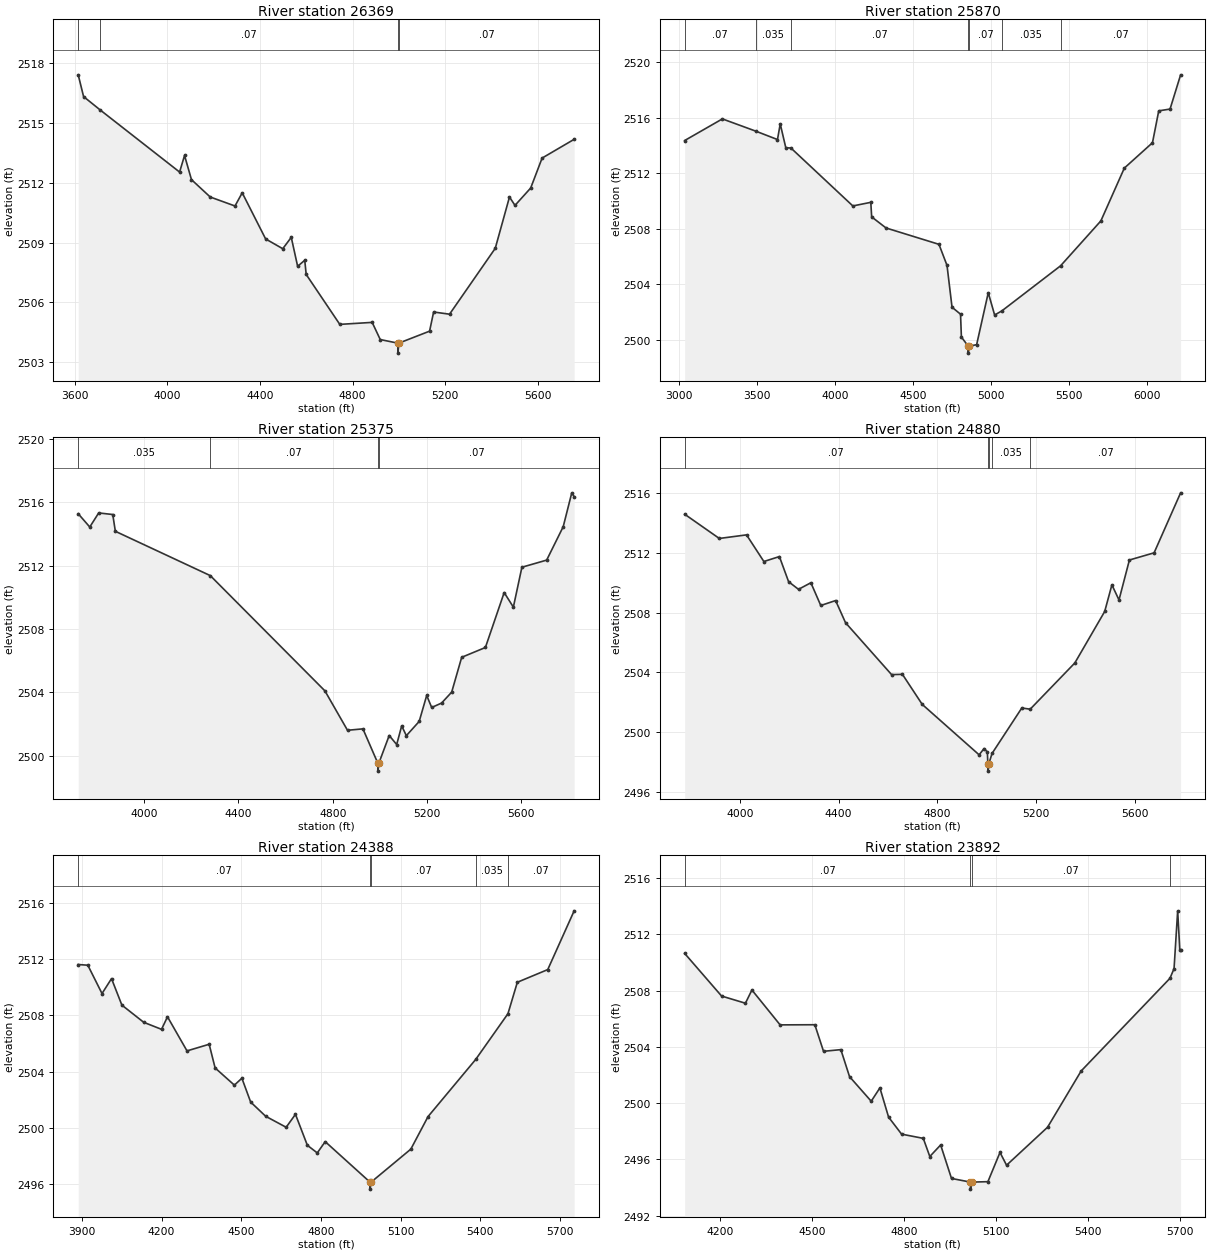
Type RM Length L Ch R = 1 ,26369   ,499,499,499
BEGIN DESCRIPTION:
Bitter Creek Trib6 52.0
END DESCRIPTION:
XS GIS Cut Line= 3
      1436254.98      6789838.04        1435545.      6791027.11
      1435804.98      6791737.96
#Sta/Elev= 30
  3615.1  2517.4  3638.3 2516.31    3710 2515.64  4052.9 2512.53  4074.3 2513.36
  4104.2 2512.15  4185.2 2511.28  4292.2 2510.83  4323.4 2511.49  4424.5 2509.18
  4498.5 2508.69  4535.2 2509.26  4562.7 2507.81  4593.4 2508.11  4599.7  2507.4
  4744.8  2504.9  4884.6    2505  4919.5 2504.14  4995.6 2503.96  4995.9 2503.46
  4999.6 2503.96  5132.5 2504.56    5150 2505.52  5218.8 2505.41  5416.2 2508.71
  5477.6 2511.28  5501.4 2510.86  5569.2 2511.73  5618.5 2513.23  5756.9 2514.17
#Mann= 4 ,-1 , 0
  3615.1    .035       0    3710     .07       0  4995.6     .07       0
  4999.6     .07       0
Bank Sta=4995.6,4999.6
XS Rating Curve= 0 ,0
Exp/Cntr=0.3,0.1

Type RM Length L Ch R = 1 ,25870   ,495,495,495
BEGIN DESCRIPTION:
Bitter Creek Trib6 51.0
END DESCRIPTION:
XS GIS Cut Line= 3
        1434355.      6789287.99      1435168.62      6791074.76
        1435255.      6792287.99
#Sta/Elev= 30
  3036.7 2514.37  3278.4 2515.93  3491.7 2515.05  3631.7 2514.44  3649.3 2515.57
    3685 2513.85  3717.9 2513.83  4114.8 2509.65    4230 2509.91  4235.5 2508.86
  4327.7 2508.06    4667 2506.88  4718.6 2505.36  4750.8 2502.34  4805.3 2501.84
  4810.8 2500.19  4854.8 2499.53    4855 2499.03    4859 2499.53  4908.5 2499.64
  4983.1 2503.39  5023.9 2501.78  5070.5 2502.08  5446.7 2505.33    5705 2508.57
  5855.4 2512.38  6035.9 2514.21    6076 2516.51  6148.5 2516.64  6216.3 2519.11
#Mann= 7 ,-1 , 0
  3036.7     .07       0  3491.7    .035       0  3717.9     .07       0
  4854.8     .07       0    4859     .07       0  5070.5    .035       0
  5446.7     .07       0
Bank Sta=4854.8,4859
XS Rating Curve= 0 ,0
Exp/Cntr=0.3,0.1

Type RM Length L Ch R = 1 ,25375   ,495,495,495
BEGIN DESCRIPTION:
Bitter Creek Trib6 50.0
END DESCRIPTION:
XS GIS Cut Line= 3
      1434455.01      6790188.02      1434831.56      6791411.07
      1435104.99      6792187.96
#Sta/Elev= 30
  3720.3 2515.29  3769.3 2514.45  3807.2 2515.34  3866.8 2515.24  3877.8 2514.18
  4280.5 2511.38  4766.6  2504.1  4862.4 2501.61  4927.8  2501.7    4991 2499.53
  4991.3 2499.03  4995.3 2499.53  5039.2 2501.28    5071 2500.71  5092.2 2501.89
  5111.9 2501.27  5166.4 2502.17  5198.2 2503.81  5219.4 2503.05  5261.4 2503.33
  5304.2 2504.02  5346.6 2506.22  5447.2 2506.84  5526.8 2510.31  5565.8 2509.39
    5602 2511.91    5707 2512.36  5777.2 2514.47  5813.5 2516.61  5823.6 2516.37
#Mann= 4 ,-1 , 0
  3720.3    .035       0  4280.5     .07       0    4991     .07       0
  4995.3     .07       0
Bank Sta=4991,4995.3
XS Rating Curve= 0 ,0
Exp/Cntr=0.3,0.1

Type RM Length L Ch R = 1 ,24880   ,492,492,492
BEGIN DESCRIPTION:
Bitter Creek Trib6 49.0
END DESCRIPTION:
XS GIS Cut Line= 3
        1434355.      6790438.01      1434435.16      6791658.38
        1434905.        6792288.
#Sta/Elev= 30
    3777 2514.57  3917.3 2512.95  4027.5 2513.19  4097.7 2511.41  4160.6 2511.74
  4197.9 2510.06    4238 2509.55  4288.1 2509.99  4328.2 2508.47  4388.3  2508.8
  4428.4 2507.32    4615 2503.85  4658.9 2503.87  4739.1 2501.86  4969.5 2498.49
  4989.6 2498.91  5002.9 2498.68  5004.8  2497.9    5005  2497.4  5009.1  2497.9
  5021.8 2498.58  5142.4 2501.62  5176.4 2501.54  5357.2 2504.63  5478.1 2508.07
  5507.3 2509.85    5536 2508.84  5578.2 2511.51  5678.2 2511.99  5785.6    2516
#Mann= 5 ,-1 , 0
    3777     .07       0  5004.8     .07       0  5009.1     .07       0
  5021.8    .035       0  5176.4     .07       0
Bank Sta=5004.8,5009.1
XS Rating Curve= 0 ,0
Exp/Cntr=0.3,0.1

Type RM Length L Ch R = 1 ,24388   ,496,496,496
BEGIN DESCRIPTION:
Bitter Creek Trib6 48.0
END DESCRIPTION:
XS GIS Cut Line= 3
      1433105.01      6791488.01      1434099.13      6791990.28
      1434704.96      6792437.97
#Sta/Elev= 30
  3886.2 2511.61  3922.4 2511.56  3975.8 2509.55  4011.6 2510.61  4050.6 2508.73
  4132.7 2507.51  4199.9 2507.01  4222.3  2507.9  4295.8 2505.48  4379.2 2505.95
  4401.6 2504.27  4474.1 2503.05  4502.4 2503.54  4535.4 2501.85    4592 2500.84
  4669.1 2500.06  4704.1 2500.98  4748.9 2498.78  4786.2 2498.24  4816.1 2499.04
  4984.6 2496.17  4984.9 2495.67  4989.1 2496.17  5138.5 2498.51  5203.3 2500.82
  5382.5 2504.87  5504.1 2508.12  5539.4 2510.35  5653.9 2511.25  5753.3 2515.42
#Mann= 5 ,-1 , 0
  3886.2     .07       0  4984.6     .07       0  4989.1     .07       0
  5382.5    .035       0  5504.1     .07       0
Bank Sta=4984.6,4989.1
XS Rating Curve= 0 ,0
Exp/Cntr=0.3,0.1

Type RM Length L Ch R = 1 ,23892   ,471,471,471
BEGIN DESCRIPTION:
Bitter Creek Trib6 47.0
END DESCRIPTION:
XS GIS Cut Line= 3
      1433104.97      6791637.97      1433749.79      6792287.57
      1434404.97      6792537.99
#Sta/Elev= 30
  4084.7 2510.64    4205 2507.61  4282.7  2507.1  4303.9 2508.04  4395.8 2505.56
    4509 2505.57  4537.3 2503.68  4593.8  2503.8  4622.1 2501.88  4692.8 2500.13
  4721.1 2501.08  4749.4    2499  4791.8 2497.79  4862.5 2497.49  4883.8  2496.2
  4919.1 2497.02  4954.5 2494.64  5016.1 2494.38  5016.4 2493.88  5020.7 2494.38
  5073.2 2494.41  5112.6 2496.49    5134 2495.58  5267.6 2498.28  5377.1 2502.28
  5666.6 2508.87    5680 2509.56  5691.8 2513.67  5698.8 2510.87  5701.4 2510.87
#Mann= 4 ,-1 , 0
  4084.7     .07       0  5016.1     .07       0  5020.7     .07       0
  5666.6    .035       0
Bank Sta=5016.1,5020.7
XS Rating Curve= 0 ,0
Exp/Cntr=0.3,0.1

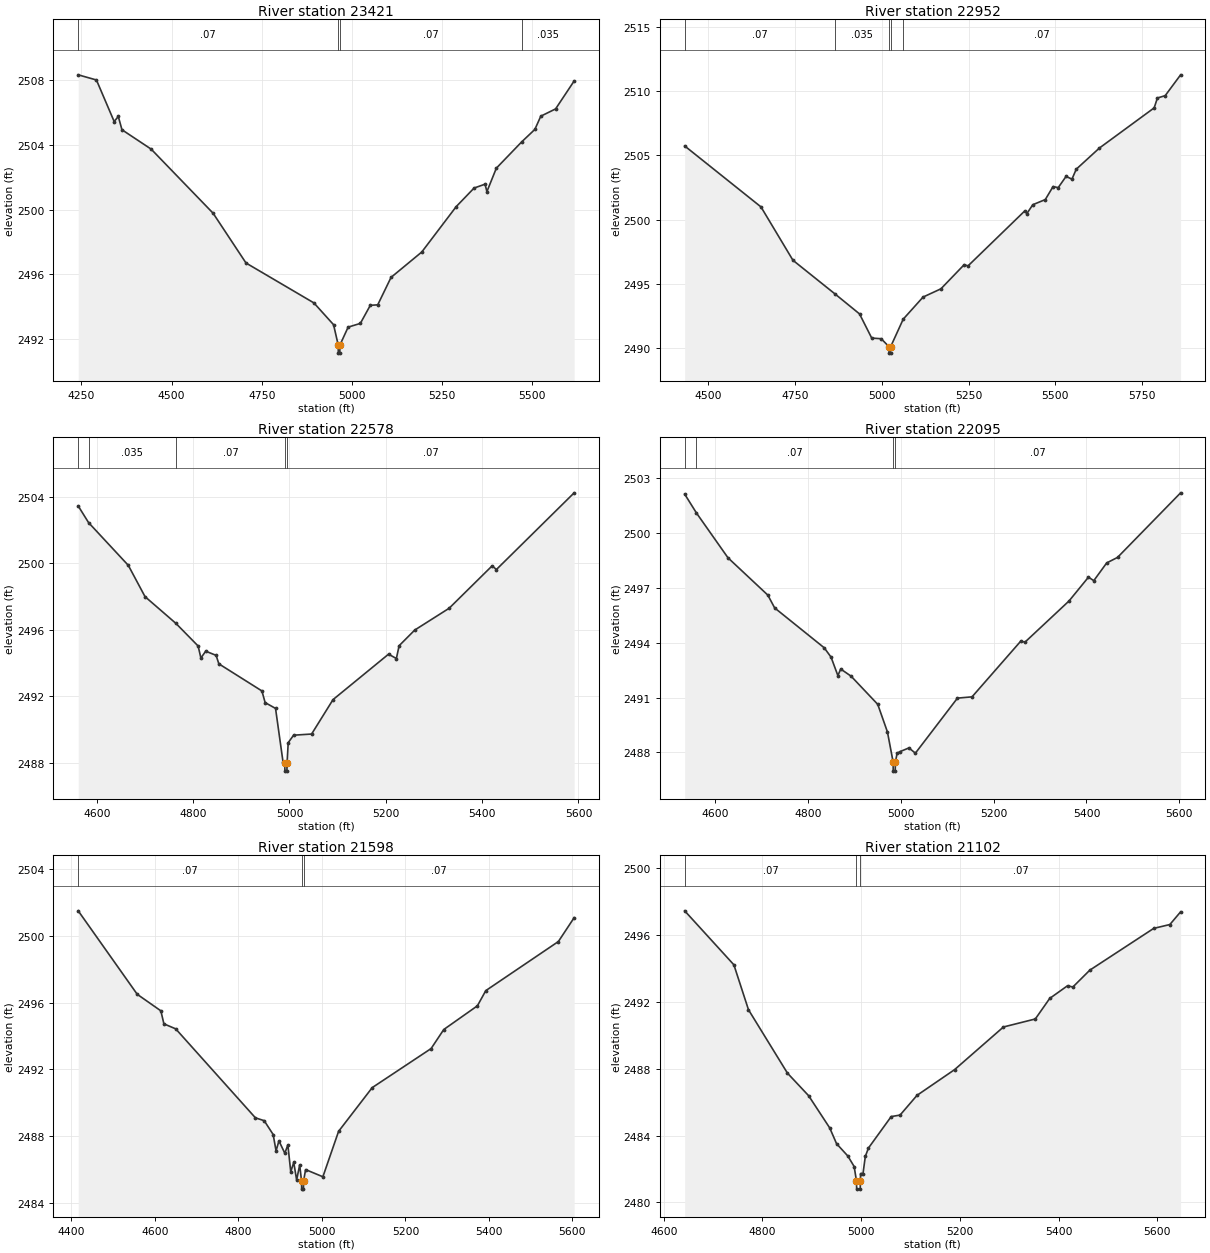
Type RM Length L Ch R = 1 ,23421   ,469,469,469
BEGIN DESCRIPTION:
Bitter Creek Trib6 46.0
END DESCRIPTION:
XS GIS Cut Line= 3
      1432855.05      6792538.01       1433605.5      6792648.17
      1434205.01        6792788.
#Sta/Elev= 30
  4241.5 2508.35    4292 2508.03  4341.1 2505.46  4352.6 2505.77  4362.7 2504.95
  4443.6 2503.75  4615.3 2499.78  4706.4  2496.7  4894.5 2494.23    4949 2492.88
  4961.9 2491.62  4962.2 2491.12  4966.3 2491.12  4966.6 2491.62  4989.4 2492.73
  5023.2 2492.96  5050.8 2494.08  5071.4 2494.11  5108.3 2495.81  5193.4 2497.38
  5288.8 2500.19  5338.3 2501.34  5368.7 2501.58  5373.9 2501.12    5400 2502.57
  5470.3  2504.2  5506.7 2504.97  5523.2 2505.79  5564.2 2506.24  5615.6 2507.97
#Mann= 4 ,-1 , 0
  4241.5     .07       0  4961.9     .07       0  4966.6     .07       0
  5470.3    .035       0
Bank Sta=4961.9,4966.6
XS Rating Curve= 0 ,0
Exp/Cntr=0.3,0.1

Type RM Length L Ch R = 1 ,22952   ,374,374,374
BEGIN DESCRIPTION:
Bitter Creek Trib6 45.0
END DESCRIPTION:
XS GIS Cut Line= 3
        1432955.        6792588.      1433331.61      6793011.31
      1434104.96      6793387.98
#Sta/Elev= 30
  4433.4 2505.72  4652.9 2500.98  4744.9 2496.83  4864.6 2494.24  4936.4 2492.66
  4971.5 2490.78  4998.8 2490.73  5021.2 2490.11  5021.5 2489.61  5025.6 2489.61
    5026 2490.11  5062.1 2492.25  5119.3 2493.97  5170.6 2494.61  5237.6 2496.49
  5248.5 2496.39  5412.3 2500.68  5417.9 2500.46  5434.9 2501.15  5470.9 2501.55
  5493.2 2502.56  5508.1 2502.48  5530.6 2503.35  5547.6 2503.14  5559.9 2503.91
  5626.7 2505.56  5784.1 2508.68  5793.5 2509.45  5815.8 2509.63  5860.2 2511.25
#Mann= 5 ,-1 , 0
  4433.4     .07       0  4864.6    .035       0  5021.2    .035       0
    5026    .035       0  5062.1     .07       0
Bank Sta=5021.2,5026
XS Rating Curve= 0 ,0
Exp/Cntr=0.3,0.1

Type RM Length L Ch R = 1 ,22578   ,483,483,483
BEGIN DESCRIPTION:
Bitter Creek Trib6 44.0
END DESCRIPTION:
XS GIS Cut Line= 3
      1432754.97      6793087.98      1433134.51       6793307.8
      1433654.98      6793587.99
#Sta/Elev= 30
  4561.4 2503.44  4582.9 2502.44  4665.4 2499.87  4700.1 2497.99  4764.3 2496.38
  4810.4 2495.02  4816.1  2494.3  4826.1 2494.71  4847.7 2494.46  4853.4 2493.95
  4942.8 2492.32  4949.5 2491.62  4971.1 2491.27  4986.8 2488.02  4990.2    2488
  4990.6  2487.5  4994.7  2487.5  4995.1    2488  4997.4 2489.21  5008.6 2489.66
    5046 2489.73  5090.5  2491.8  5205.7 2494.53    5222 2494.27  5227.7 2495.04
  5260.1 2495.98  5331.5 2497.29  5420.8 2499.84  5429.7 2499.62  5591.1 2504.23
#Mann= 5 ,-1 , 0
  4561.4     .07       0  4582.9    .035       0  4764.3     .07       0
  4990.2     .07       0  4995.1     .07       0
Bank Sta=4990.2,4995.1
XS Rating Curve= 0 ,0
Exp/Cntr=0.3,0.1

Type RM Length L Ch R = 1 ,22095   ,497,497,497
BEGIN DESCRIPTION:
Bitter Creek Trib6 43.0
END DESCRIPTION:
XS GIS Cut Line= 3
      1432605.01      6793288.01      1432877.86      6793664.43
      1433455.02      6793838.01
#Sta/Elev= 30
  4535.1 2502.12  4560.4 2501.09  4628.3 2498.64  4714.1  2496.6  4728.8  2495.9
  4835.5 2493.72  4850.2 2493.21  4864.9  2492.2    4871 2492.56  4893.3 2492.17
  4950.7 2490.63  4971.6 2489.12  4983.8 2487.48  4984.1 2486.98  4988.3 2486.98
  4988.7 2487.48  4992.4 2487.96  4999.1 2488.05  5017.9 2488.25  5031.7 2487.96
  5122.3 2490.97  5153.7 2491.04  5258.1 2494.07  5268.1 2494.04  5362.5 2496.28
  5404.3 2497.58  5415.8 2497.39  5443.6 2498.36  5466.9 2498.66  5602.7 2502.19
#Mann= 4 ,-1 , 0
  4535.1    .035       0  4560.4     .07       0  4983.8     .07       0
  4988.7     .07       0
Bank Sta=4983.8,4988.7
XS Rating Curve= 0 ,0
Exp/Cntr=0.3,0.1

Type RM Length L Ch R = 1 ,21598   ,496,496,496
BEGIN DESCRIPTION:
Bitter Creek Trib6 42.0
END DESCRIPTION:
XS GIS Cut Line= 3
      1432305.01      6793638.01       1432705.4        6794063.
      1433305.03        6794138.
#Sta/Elev= 30
  4416.1  2501.5  4557.5  2496.5  4614.1 2495.51  4621.4 2494.73  4649.7 2494.43
  4840.7  2489.1  4861.7 2488.93  4883.2  2488.1  4890.1 2487.12    4897 2487.72
  4911.1 2486.98  4918.4 2487.48  4925.3 2485.87  4932.5 2486.43  4939.4 2485.38
  4946.7 2486.28  4951.1 2485.33  4951.5 2484.83  4955.7 2484.83  4956.1 2485.33
  4960.9    2486  5002.3 2485.57  5039.9 2488.29  5120.5 2490.91  5261.6 2493.25
  5291.9 2494.39  5372.5 2495.81  5392.6 2496.72  5566.5 2499.66  5604.3 2501.09
#Mann= 3 ,-1 , 0
  4416.1     .07       0  4951.1     .07       0  4956.1     .07       0
Bank Sta=4951.1,4956.1
XS Rating Curve= 0 ,0
Exp/Cntr=0.3,0.1

Type RM Length L Ch R = 1 ,21102   ,499,499,499
BEGIN DESCRIPTION:
Bitter Creek Trib6 41.0
END DESCRIPTION:
XS GIS Cut Line= 3
      1432105.01        6794138.      1432396.96      6794344.33
      1432654.99      6794937.98
#Sta/Elev= 30
  4642.5 2497.45  4742.2 2494.22  4771.8 2491.53  4850.7 2487.74  4893.6 2486.39
  4936.4 2484.46  4950.2 2483.52  4973.1 2482.78  4985.9 2482.15  4990.5  2481.3
    4991  2480.8  4998.1  2480.8  4998.6  2481.3  4998.8 2481.73  5003.8 2481.73
  5008.5 2482.76  5014.9 2483.26  5060.9 2485.14  5078.9 2485.23  5113.2 2486.41
  5189.4 2487.95  5288.3  2490.5  5352.9 2490.98  5382.1 2492.21  5418.3 2492.97
  5428.9 2492.89  5463.3  2493.9  5592.8  2496.4  5625.5 2496.63  5647.3 2497.39
#Mann= 3 ,-1 , 0
  4642.5     .07       0  4990.5     .07       0  4998.6     .07       0
Bank Sta=4990.5,4998.6
XS Rating Curve= 0 ,0
Exp/Cntr=0.3,0.1

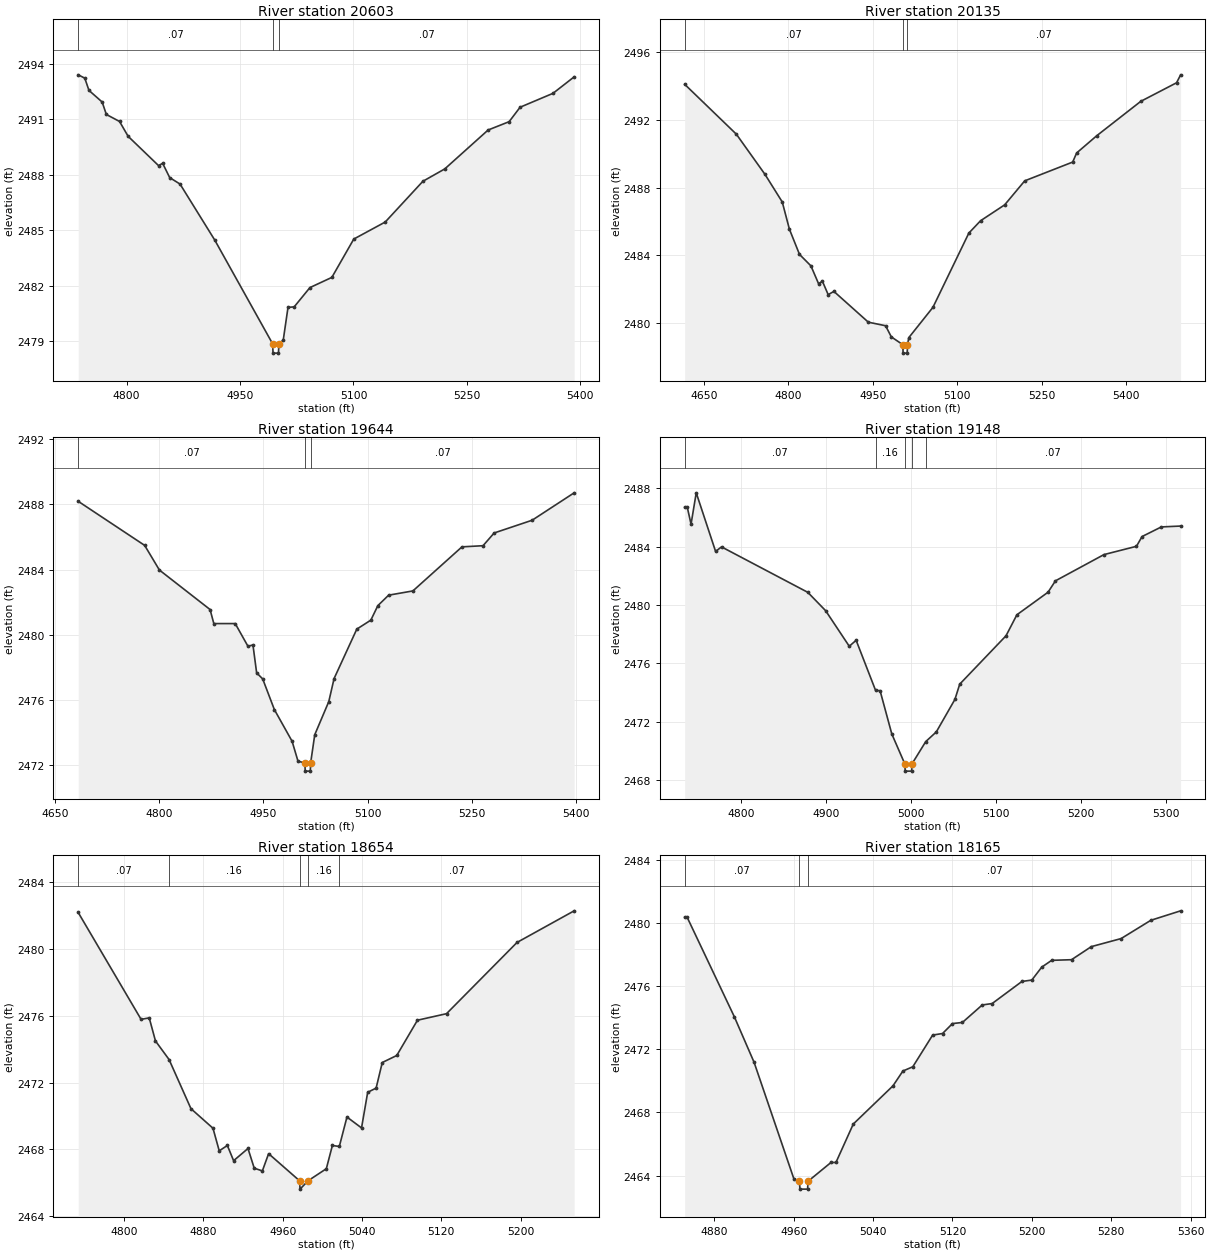
Type RM Length L Ch R = 1 ,20603   ,468,468,468
BEGIN DESCRIPTION:
Bitter Creek Trib6 40.0
END DESCRIPTION:
XS GIS Cut Line= 3
      1431855.04      6794588.02      1432095.12      6794698.05
      1432404.99      6794937.99
#Sta/Elev= 30
  4735.9  2493.4  4744.6 2493.22  4750.1 2492.56  4767.6 2491.93  4773.1 2491.26
  4790.6 2490.88  4801.9 2490.08  4842.1  2488.5  4847.6 2488.62  4856.9 2487.85
  4870.6  2487.5  4916.6 2484.47  4993.1 2478.87  4993.6 2478.37  5000.8 2478.37
  5001.3 2478.87  5007.1 2479.07  5013.4 2480.84  5021.6 2480.87  5042.4 2481.91
  5071.4 2482.46  5100.4 2484.53    5142 2485.45  5191.8 2487.65  5220.8 2488.32
  5278.1 2490.42  5305.9 2490.87  5320.4 2491.65  5363.9  2492.4  5391.9 2493.29
#Mann= 3 ,-1 , 0
  4735.9     .07       0  4993.1     .07       0  5001.3     .07       0
Bank Sta=4993.1,5001.3
XS Rating Curve= 0 ,0
Exp/Cntr=0.3,0.1

Type RM Length L Ch R = 1 ,20135   ,491,491,491
BEGIN DESCRIPTION:
Bitter Creek Trib6 39.0
END DESCRIPTION:
XS GIS Cut Line= 3
        1431705.      6794637.98      1431778.31      6795014.92
      1432155.03      6795338.02
#Sta/Elev= 30
    4616 2494.11  4707.7 2491.16  4758.6 2488.78  4789.2 2487.15  4801.9 2485.54
  4819.8 2484.05  4840.1 2483.37  4853.6 2482.32  4860.5 2482.46  4870.7 2481.67
  4880.9 2481.86    4942 2480.04  4972.6 2479.83  4982.8 2479.17  5003.2 2478.71
  5003.7 2478.21    5011 2478.21  5011.5 2478.71  5013.9 2479.13  5056.7 2480.92
  5120.4 2485.31  5141.2 2486.04    5184 2486.98  5219.6  2488.4  5304.7 2489.51
  5311.8 2490.05  5347.5 2491.07  5425.5  2493.1  5489.1  2494.2  5496.3 2494.67
#Mann= 3 ,-1 , 0
    4616     .07       0  5003.2     .07       0  5011.5     .07       0
Bank Sta=5003.2,5011.5
XS Rating Curve= 0 ,0
Exp/Cntr=0.3,0.1

Type RM Length L Ch R = 1 ,19644   ,496,496,496
BEGIN DESCRIPTION:
Bitter Creek Trib6 38.0
END DESCRIPTION:
XS GIS Cut Line= 3
      1431404.99      6795087.98      1431511.11      6795385.84
      1431904.97        6795438.
#Sta/Elev= 30
  4683.8 2488.18  4779.4 2485.48  4800.6 2483.97  4873.5 2481.55  4878.9 2480.69
  4909.7 2480.69    4928  2479.3  4935.2 2479.38  4940.5 2477.67  4949.2  2477.3
    4966 2475.42  4991.5 2473.48    5000 2472.26  5009.9 2472.15  5010.4 2471.65
  5017.7 2471.65  5018.2 2472.15  5024.1 2473.88  5044.3 2475.91  5051.9 2477.32
  5084.6 2480.35  5104.8  2480.9  5114.9 2481.79  5130.4 2482.43  5165.3 2482.69
  5235.9 2485.39  5266.2 2485.46  5282.2 2486.24  5336.8 2487.02  5397.3  2488.7
#Mann= 3 ,-1 , 0
  4683.8     .07       0  5009.9     .07       0  5018.2     .07       0
Bank Sta=5009.9,5018.2
XS Rating Curve= 0 ,0
Exp/Cntr=0.3,0.1

Type RM Length L Ch R = 1 ,19148   ,494,494,494
BEGIN DESCRIPTION:
Bitter Creek Trib6 37.0
END DESCRIPTION:
XS GIS Cut Line= 3
      1430904.96      6795487.98      1431125.13      6795638.32
      1431405.01      6795788.01
#Sta/Elev= 30
  4733.4  2486.7  4736.5  2486.7  4740.9 2485.55    4747  2487.7  4769.8 2483.68
  4776.8 2483.99  4878.4 2480.87  4899.4 2479.61  4927.2 2477.17  4935.3 2477.58
  4958.2 2474.14  4963.5 2474.12  4977.3 2471.15  4992.6  2469.1  4993.1  2468.6
  5000.6  2468.6  5001.1  2469.1  5017.3 2470.63  5029.7 2471.29  5051.6 2473.52
  5057.3 2474.57  5111.8 2477.89  5124.6 2479.33  5161.3 2480.88    5170 2481.66
  5227.1 2483.46  5265.4 2484.03    5272  2484.7  5294.7 2485.36  5317.4 2485.42
#Mann= 5 ,-1 , 0
  4733.4     .07       0  4958.2     .16       0  4992.6     .07       0
  5001.1     .16       0  5017.3     .07       0
Bank Sta=4992.6,5001.1
XS Rating Curve= 0 ,0
Exp/Cntr=0.3,0.1

Type RM Length L Ch R = 1 ,18654   ,489,489,489
BEGIN DESCRIPTION:
Bitter Creek Trib6 36.0
END DESCRIPTION:
XS GIS Cut Line= 3
      1430604.97      6795787.98      1430799.83      6795938.46
      1431005.02      6796088.01
#Sta/Elev= 30
  4753.8 2482.17  4817.2 2475.78  4825.4 2475.87  4831.7 2474.49  4845.4 2473.38
  4867.5 2470.44  4889.7 2469.27    4896 2467.92  4904.2 2468.24  4910.5 2467.33
    4925 2468.06  4931.3 2466.88  4939.5 2466.72  4945.8 2467.75    4977 2466.13
  4977.5 2465.63  4985.6 2466.13    5004 2466.85  5010.1 2468.24  5017.1 2468.18
  5024.8 2469.94  5039.5 2469.29  5045.7 2471.42  5054.2 2471.67  5060.4  2473.2
    5075 2473.62  5095.9 2475.73  5125.2 2476.12  5196.3 2480.38  5253.9 2482.27
#Mann= 5 ,-1 , 0
  4753.8     .07       0  4845.4     .16       0    4977     .07       0
  4985.6     .16       0  5017.1     .07       0
Bank Sta=4977,4985.6
XS Rating Curve= 0 ,0
Exp/Cntr=0.3,0.1

Type RM Length L Ch R = 1 ,18165   ,453,453,453
BEGIN DESCRIPTION:
Bitter Creek Trib6 35.0
END DESCRIPTION:
XS GIS Cut Line= 3
        1430405.        6796188.        1430555.        6796188.
        1430905.        6796188.
#Sta/Elev= 30
    4850 2480.38  4852.5 2480.38    4900 2474.08    4920 2471.18    4960 2463.81
  4965.7 2463.64  4966.2 2463.14  4973.9 2463.14  4974.4 2463.64  4997.5 2464.83
  5002.5 2464.83    5020 2467.27    5060 2469.69    5070 2470.63    5080  2470.9
    5100 2472.91    5110 2473.01    5120 2473.64    5130 2473.71    5150 2474.82
    5160 2474.91    5190 2476.31    5200  2476.4    5210 2477.22    5220 2477.65
    5240 2477.69    5260 2478.52    5290 2479.03    5320 2480.19    5350 2480.79
#Mann= 3 ,-1 , 0
    4850     .07       0  4965.7     .07       0  4974.4     .07       0
Bank Sta=4965.7,4974.4
XS Rating Curve= 0 ,0
Exp/Cntr=0.3,0.1

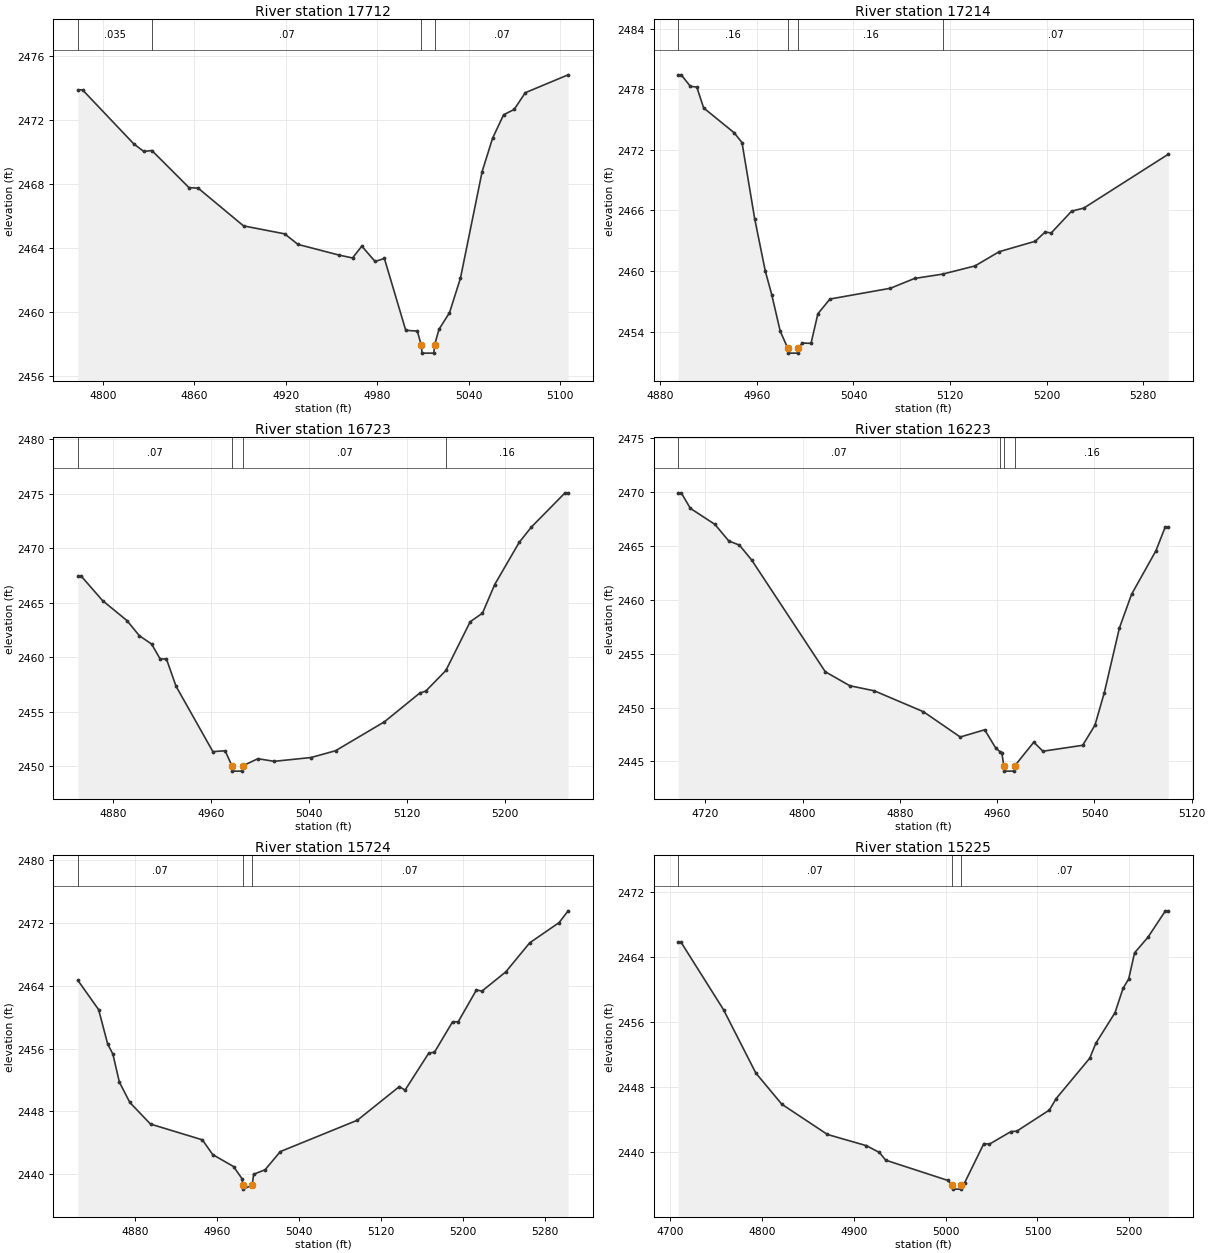
Type RM Length L Ch R = 1 ,17712   ,498,498,498
BEGIN DESCRIPTION:
Bitter Creek Trib6 34.0
END DESCRIPTION:
XS GIS Cut Line= 3
        1430455.        6796438.      1430579.04      6796615.33
      1430654.98      6796687.98
#Sta/Elev= 30
  4783.6  2473.9  4786.6  2473.9  4820.2 2470.52  4826.8 2470.04  4832.1  2470.1
  4856.4 2467.78  4862.5 2467.74  4892.2 2465.38  4919.2 2464.88  4927.9 2464.22
  4954.9 2463.55  4963.7 2463.37  4969.8 2464.11  4978.5 2463.15  4984.6 2463.34
  4998.6 2458.84  5006.2 2458.79  5008.8 2457.91  5009.3 2457.41    5017 2457.41
  5017.5 2457.91  5020.4  2458.9  5027.3 2459.94  5034.5 2462.11  5048.7 2468.78
  5055.6 2470.88  5062.8 2472.34  5069.7 2472.67    5077 2473.72  5105.1 2474.84
#Mann= 4 ,-1 , 0
  4783.6    .035       0  4832.1     .07       0  5008.8     .07       0
  5017.5     .07       0
Bank Sta=5008.8,5017.5
XS Rating Curve= 0 ,0
Exp/Cntr=0.3,0.1

Type RM Length L Ch R = 1 ,17214   ,491,491,491
BEGIN DESCRIPTION:
Bitter Creek Trib6 33.0
END DESCRIPTION:
XS GIS Cut Line= 3
      1430105.01      6796788.01      1430204.51      6796822.79
      1430505.02        6796838.
#Sta/Elev= 30
  4894.6 2479.44  4897.2 2479.44  4904.8  2478.3  4910.1 2478.23  4915.8 2476.16
  4941.1  2473.7  4947.6 2472.72  4958.1 2465.18  4966.9 2459.99  4972.2 2457.67
  4979.3 2454.02  4985.5 2452.36    4986 2451.86  4993.8 2451.86  4994.3 2452.36
  4997.6 2452.86  5004.8 2452.83  5010.5 2455.77  5020.5 2457.22  5070.6 2458.29
  5090.6 2459.26  5113.8 2459.69  5140.7  2460.5  5160.7 2461.91  5190.7 2462.95
  5198.8 2463.86  5203.9 2463.77  5220.8 2465.93  5230.8 2466.23  5300.9 2471.57
#Mann= 4 ,-1 , 0
  4894.6     .16       0  4985.5     .07       0  4994.3     .16       0
  5113.8     .07       0
Bank Sta=4985.5,4994.3
XS Rating Curve= 0 ,0
Exp/Cntr=0.3,0.1

Type RM Length L Ch R = 1 ,16723   ,500,500,500
BEGIN DESCRIPTION:
Bitter Creek Trib6 32.0
END DESCRIPTION:
XS GIS Cut Line= 3
      1430104.97        6797288.      1430253.28      6797298.71
      1430504.95        6797288.
#Sta/Elev= 30
  4851.3 2467.47  4853.8 2467.47  4871.4  2465.2  4891.4 2463.36  4901.5 2461.97
  4911.5 2461.21  4918.6 2459.82  4923.6 2459.85  4931.5 2457.33  4961.6 2451.33
  4971.6 2451.41  4977.1 2450.04  4977.6 2449.54  4985.7 2449.54  4986.2 2450.04
  4998.4 2450.68  5011.7 2450.44  5041.8 2450.79  5061.8 2451.41  5101.8 2454.07
  5130.6  2456.7  5135.6 2456.89    5152 2458.78  5171.9 2463.26  5181.9 2464.04
  5191.9 2466.67  5211.9 2470.54  5221.9 2471.95  5249.4 2475.09  5251.9 2475.09
#Mann= 4 ,-1 , 0
  4851.3     .07       0  4977.1     .07       0  4986.2     .07       0
    5152     .16       0
Bank Sta=4977.1,4986.2
XS Rating Curve= 0 ,0
Exp/Cntr=0.3,0.1

Type RM Length L Ch R = 1 ,16223   ,499,499,499
BEGIN DESCRIPTION:
Bitter Creek Trib6 31.0
END DESCRIPTION:
XS GIS Cut Line= 3
      1429904.97        6797638.      1430204.83      6797677.89
      1430305.02        6797688.
#Sta/Elev= 30
  4697.5 2469.95  4700.1 2469.95  4707.6 2468.51  4727.8 2467.02  4739.2 2465.48
    4748 2465.09  4758.1  2463.7  4818.6 2453.33  4838.8 2452.03  4858.9 2451.56
  4899.3 2449.62  4929.6 2447.27  4949.7 2447.94  4958.8 2446.24  4962.7 2445.87
  4963.9 2445.75  4965.4  2444.6  4965.9  2444.1    4974  2444.1  4974.5  2444.6
  4990.1 2446.79  4997.6 2445.95  5030.3  2446.5  5040.4 2448.37  5048.1 2451.39
  5060.5 2457.39  5070.5 2460.52  5090.6 2464.58  5098.2 2466.78  5100.7 2466.78
#Mann= 4 ,-1 , 0
  4697.5     .07       0  4962.7     .16       0  4965.4     .07       0
  4974.5     .16       0
Bank Sta=4965.4,4974.5
XS Rating Curve= 0 ,0
Exp/Cntr=0.3,0.1

Type RM Length L Ch R = 1 ,15724   ,499,499,499
BEGIN DESCRIPTION:
Bitter Creek Trib6 30.0
END DESCRIPTION:
XS GIS Cut Line= 3
      1429805.03        6798038.      1429978.77      6798064.85
      1430254.96      6798187.98
#Sta/Elev= 30
  4824.2 2464.69  4844.4 2460.97  4853.2  2456.6  4858.3 2455.31  4864.6 2451.75
  4874.8 2449.15    4895 2446.39  4945.6 2444.38  4955.7  2442.5    4976 2440.98
  4984.5 2439.39  4984.9  2438.6  4985.4  2438.1  4994.2  2438.6  4995.6 2439.99
  5006.8 2440.57  5021.6 2442.88  5096.8 2446.88  5137.8 2451.17  5143.3 2450.71
  5166.5 2455.44    5172 2455.54  5189.7 2459.42  5195.2 2459.43  5212.9 2463.47
  5218.4 2463.34  5241.6 2465.78  5264.9 2469.48  5293.6 2472.06  5302.4 2473.56
#Mann= 3 ,-1 , 0
  4824.2     .07       0  4984.9     .07       0  4994.2     .07       0
Bank Sta=4984.9,4994.2
XS Rating Curve= 0 ,0
Exp/Cntr=0.3,0.1

Type RM Length L Ch R = 1 ,15225   ,496,496,496
BEGIN DESCRIPTION:
Bitter Creek Trib6 29.0
END DESCRIPTION:
XS GIS Cut Line= 3
      1429605.03      6798288.03      1429806.55      6798498.64
      1430005.01      6798638.01
#Sta/Elev= 30
  4708.5 2465.75  4711.9 2465.75    4758 2457.49  4793.2  2449.7  4821.5 2445.87
  4871.2 2442.15  4913.7 2440.77  4927.8 2439.94  4934.7 2438.99  5002.1 2436.51
  5007.3 2435.93  5007.8 2435.43  5016.2 2435.43  5016.7 2435.93  5020.7 2436.22
  5041.6 2441.03  5047.7 2440.96  5071.2 2442.51  5077.4 2442.55  5113.1 2445.16
  5120.3 2446.55    5157 2451.53  5163.6 2453.36  5184.5 2457.12  5193.2  2460.1
  5199.4 2461.27  5205.8 2464.48  5220.3 2466.38  5239.4 2469.64  5242.5 2469.64
#Mann= 3 ,-1 , 0
  4708.5     .07       0  5007.3     .07       0  5016.7     .07       0
Bank Sta=5007.3,5016.7
XS Rating Curve= 0 ,0
Exp/Cntr=0.3,0.1

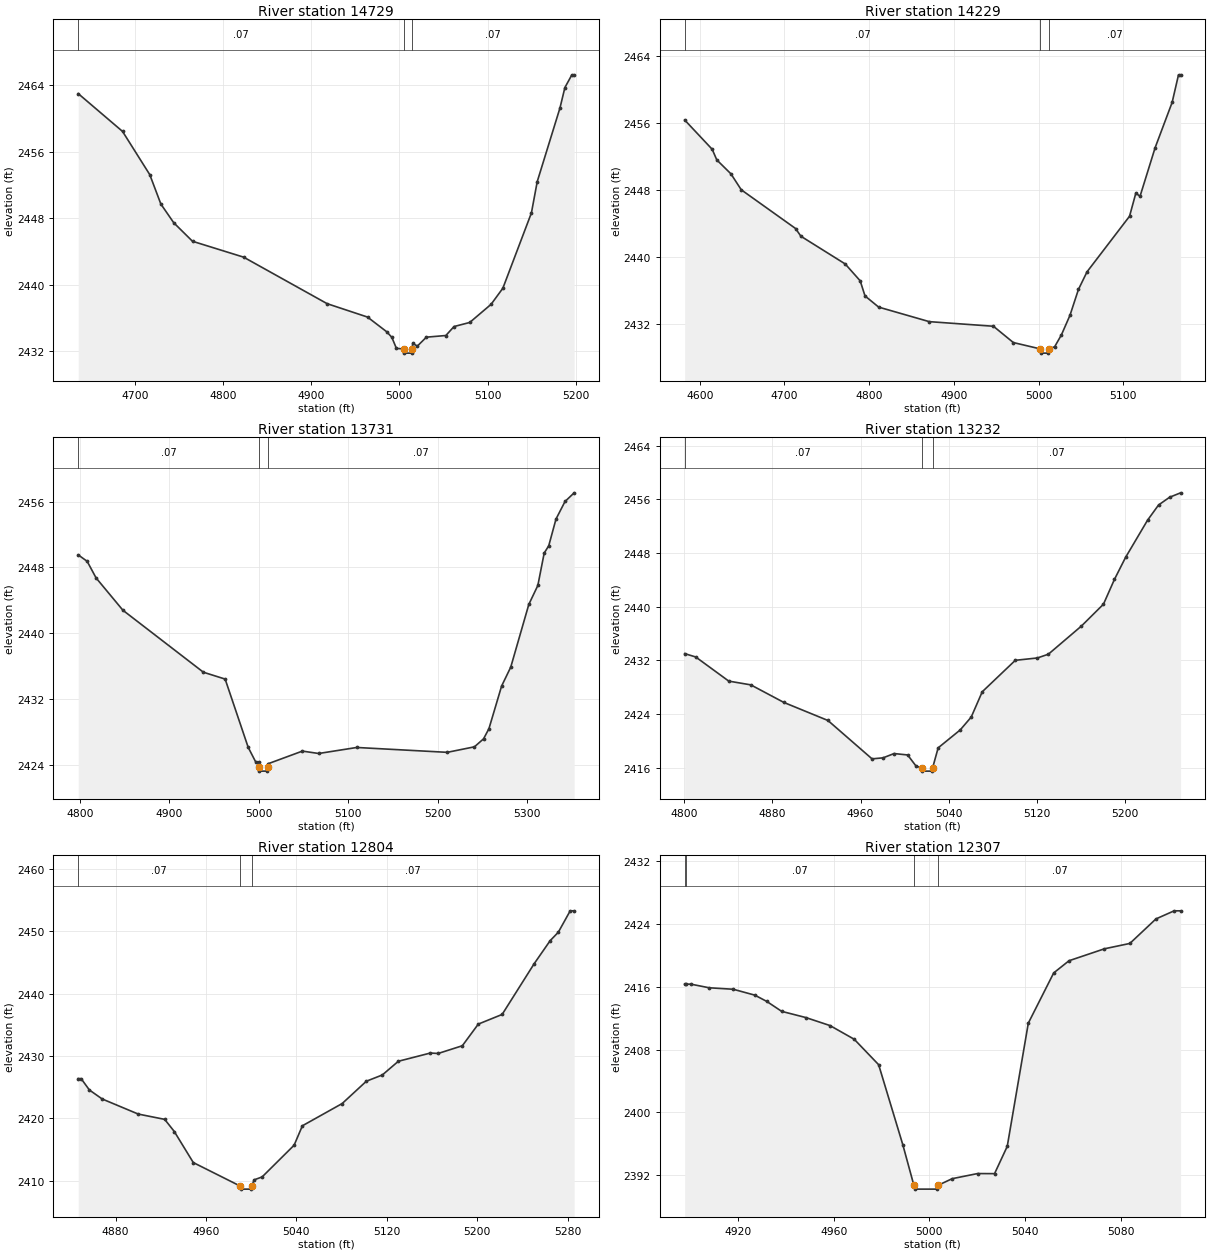
Type RM Length L Ch R = 1 ,14729   ,500,500,500
BEGIN DESCRIPTION:
Bitter Creek Trib6 28.0
END DESCRIPTION:
XS GIS Cut Line= 3
        1429305.        6798738.      1429615.85      6798928.35
      1429804.97      6798987.99
#Sta/Elev= 30
  4635.5 2462.99  4685.8 2458.44  4716.7 2453.24  4729.3  2449.7  4743.9 2447.45
  4765.2 2445.22  4823.2 2443.31    4918 2437.71  4963.8  2436.1  4985.6 2434.33
  4991.4 2433.66  4996.6 2432.33  5004.7 2432.26  5005.2 2431.76  5013.9 2431.76
  5014.4 2432.26  5015.1 2432.92  5020.4 2432.61  5030.6 2433.68  5052.7 2433.88
    5062 2434.96  5079.8 2435.45    5104 2437.63  5117.4 2439.57  5149.8 2448.63
  5156.4  2452.4  5182.2 2461.26  5187.8 2463.72  5195.7 2465.25  5198.3 2465.25
#Mann= 3 ,-1 , 0
  4635.5     .07       0  5004.7     .07       0  5014.4     .07       0
Bank Sta=5004.7,5014.4
XS Rating Curve= 0 ,0
Exp/Cntr=0.3,0.1

Type RM Length L Ch R = 1 ,14229   ,498,498,498
BEGIN DESCRIPTION:
Bitter Creek Trib6 27.0
END DESCRIPTION:
XS GIS Cut Line= 3
      1429154.96      6799237.98      1429538.11      6799404.58
      1429704.99        6799388.
#Sta/Elev= 30
  4582.2 2456.33  4614.7 2452.84  4620.1 2451.58  4636.8 2449.92    4649 2448.02
  4713.1 2443.41  4719.4 2442.49  4771.7 2439.19  4789.4 2437.18  4795.1 2435.38
  4811.2 2434.05  4870.9 2432.32  4946.7 2431.77  4970.2 2429.83  5002.1 2429.07
  5002.6 2428.57  5011.3 2428.57  5011.8 2429.07    5019 2429.33    5027 2430.75
  5037.1 2433.08  5047.1 2436.16  5057.2 2438.25  5107.4 2444.87  5114.8 2447.61
  5119.8 2447.25  5137.6 2453.03  5157.7 2458.43  5165.2 2461.71  5167.7 2461.71
#Mann= 3 ,-1 , 0
  4582.2     .07       0  5002.1     .07       0  5011.8     .07       0
Bank Sta=5002.1,5011.8
XS Rating Curve= 0 ,0
Exp/Cntr=0.3,0.1

Type RM Length L Ch R = 1 ,13731   ,499,499,499
BEGIN DESCRIPTION:
Bitter Creek Trib6 26.0
END DESCRIPTION:
XS GIS Cut Line= 3
      1429155.04        6799838.      1429356.74      6799844.16
      1429705.04      6799787.99
#Sta/Elev= 30
  4798.2 2449.53  4808.2 2448.75  4818.2 2446.73  4848.2 2442.81  4938.2 2435.29
  4962.5 2434.46  4988.3 2426.17  4996.6 2424.42    5000 2424.42  5000.4 2423.79
  5000.9 2423.29  5009.7 2423.29  5010.2 2423.79  5010.4 2424.18  5048.9 2425.72
  5067.1 2425.43  5109.7 2426.16  5210.9 2425.57  5241.3 2426.24  5251.5 2427.21
  5257.5 2428.44  5271.7 2433.62  5281.9 2435.91  5302.1 2443.52  5312.2 2445.82
  5319.3 2449.75  5324.4 2450.64  5332.5 2453.88  5342.6 2456.01  5352.8 2457.06
#Mann= 3 ,-1 , 0
  4798.2     .07       0  5000.4     .07       0  5010.2     .07       0
Bank Sta=5000.4,5010.2
XS Rating Curve= 0 ,0
Exp/Cntr=0.3,0.1

Type RM Length L Ch R = 1 ,13232   ,428,428,428
BEGIN DESCRIPTION:
Bitter Creek Trib6 25.0
END DESCRIPTION:
XS GIS Cut Line= 3
        1429405.        6800188.       1429604.6      6800188.17
        1429855.        6800188.
#Sta/Elev= 30
  4800.4    2433  4810.4  2432.5  4840.4  2428.9  4860.4 2428.34  4890.4 2425.72
  4930.4 2423.03  4970.4 2417.31  4980.4 2417.46  4990.4  2418.1  5002.7 2417.89
  5010.4 2416.22  5015.4 2415.98  5015.9 2415.48  5024.9 2415.48  5025.4 2415.98
  5030.4 2418.95  5050.4 2421.62  5060.4 2423.54  5070.4 2427.31  5100.4    2432
  5120.4 2432.35  5130.4 2432.91  5160.4 2437.11  5180.4 2440.37  5190.4 2444.08
  5200.4 2447.33  5220.4 2452.89  5230.4 2455.16  5240.4 2456.31  5250.4 2456.97
#Mann= 3 ,-1 , 0
  4800.4     .07       0  5015.4     .07       0  5025.4     .07       0
Bank Sta=5015.4,5025.4
XS Rating Curve= 0 ,0
Exp/Cntr=0.3,0.1

Type RM Length L Ch R = 1 ,12804   ,497,497,497
BEGIN DESCRIPTION:
Bitter Creek Trib6 24.0
END DESCRIPTION:
XS GIS Cut Line= 3
      1429555.05      6800637.98      1429698.88      6800585.82
      1429905.01      6800387.99
#Sta/Elev= 30
    4847 2426.38  4849.6 2426.38  4856.9 2424.56  4868.2 2423.12  4900.1  2420.7
  4923.5 2419.85    4932  2417.9  4948.8 2412.92  4990.2 2409.16  4990.7 2408.66
  4999.8 2408.66  5000.3 2409.16  5002.8 2410.16  5009.7 2410.62    5038 2415.71
  5045.3 2418.82  5080.5 2422.39  5101.9 2425.97    5116 2426.97  5130.2 2429.17
  5158.5 2430.49  5165.4 2430.42  5186.8 2431.66  5200.9 2435.13    5222 2436.68
  5250.3 2444.81  5264.5 2448.52  5271.7 2449.87  5282.2  2453.3  5285.7  2453.3
#Mann= 3 ,-1 , 0
    4847     .07       0  4990.2     .07       0  5000.3     .07       0
Bank Sta=4990.2,5000.3
XS Rating Curve= 0 ,0
Exp/Cntr=0.3,0.1

Type RM Length L Ch R = 1 ,12307   ,498,498,498
BEGIN DESCRIPTION:
Bitter Creek Trib6 23.0
END DESCRIPTION:
XS GIS Cut Line= 3
      1429854.97      6800988.01        1429956.      6800972.59
      1430055.03      6800937.99
#Sta/Elev= 29
  4897.8 2416.32  4898.3 2416.32  4900.4 2416.32    4908 2415.86  4918.1 2415.67
  4927.1 2414.92  4932.1 2414.12  4938.3 2412.86  4948.4 2412.07  4958.5 2411.05
  4968.6 2409.31  4978.8 2406.07  4988.9 2395.88  4993.5 2390.74    4994 2390.24
  5003.2 2390.24  5003.7 2390.74  5009.5 2391.57  5020.1 2392.22  5027.2 2392.21
  5032.5 2395.68  5041.3 2411.36  5051.9 2417.75  5058.3  2419.3  5073.1 2420.82
  5083.7  2421.5  5094.6 2424.62  5102.2 2425.65  5104.9 2425.65
#Mann= 4 ,-1 , 0
  4897.8     .16       0  4898.3     .07       0  4993.5     .07       0
  5003.7     .07       0
Bank Sta=4993.5,5003.7
XS Rating Curve= 0 ,0
Exp/Cntr=0.3,0.1