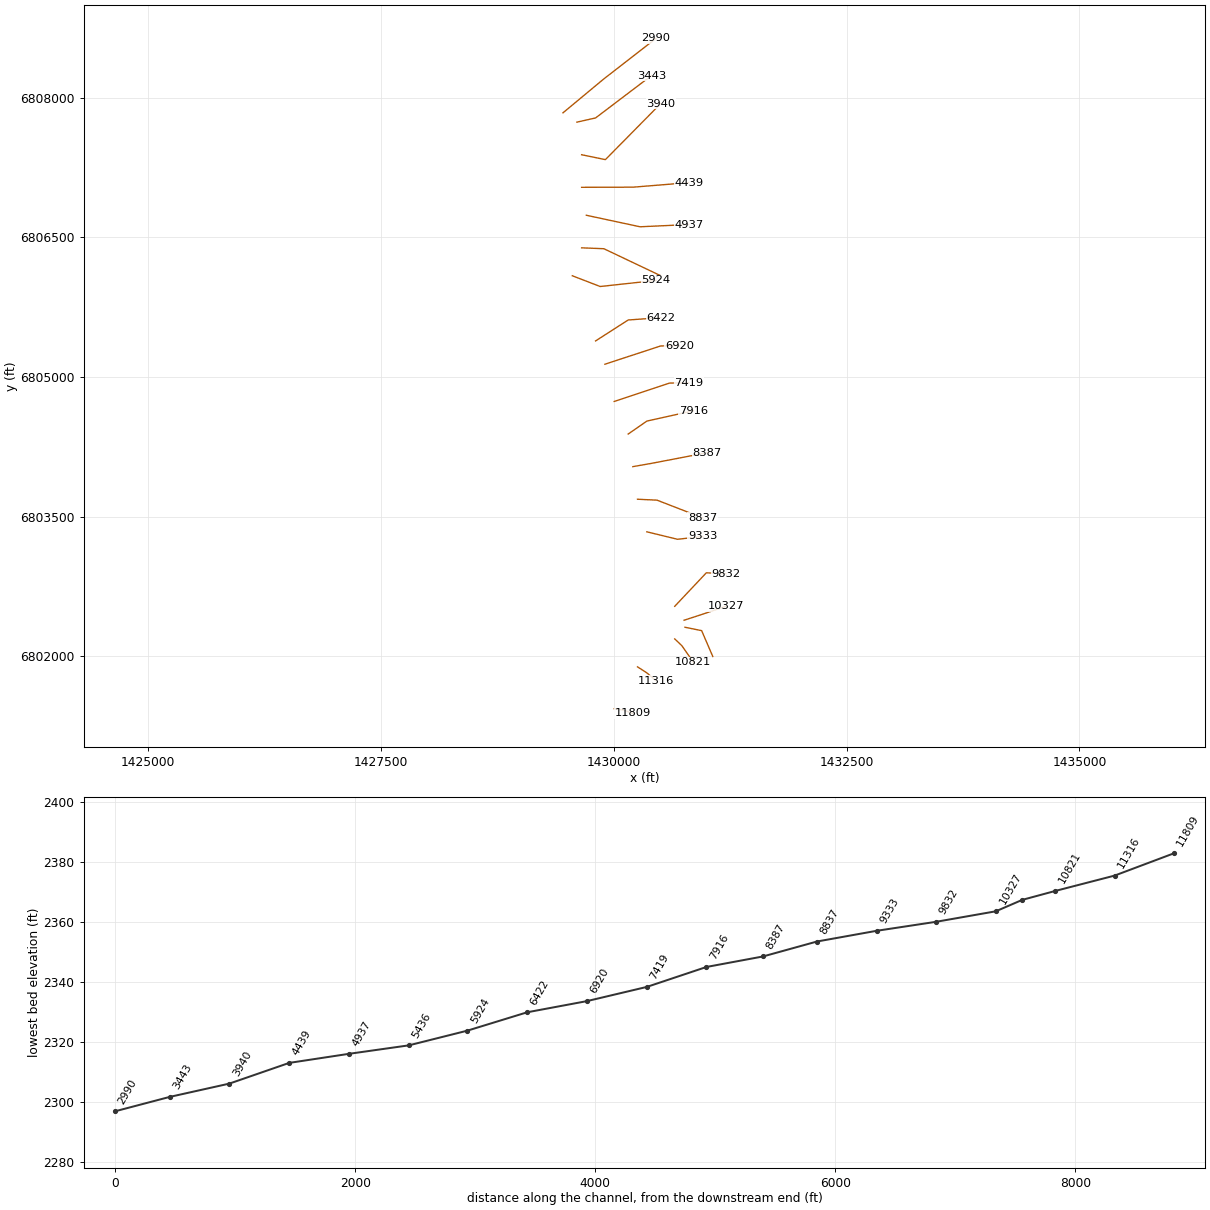
HEC-RAS study Bitter Creek Trib6.prj: Bitter Creek Trib6 Base Level Engineering

--- Bitter Creek Trib6.g01 (geometry) --- (continued)

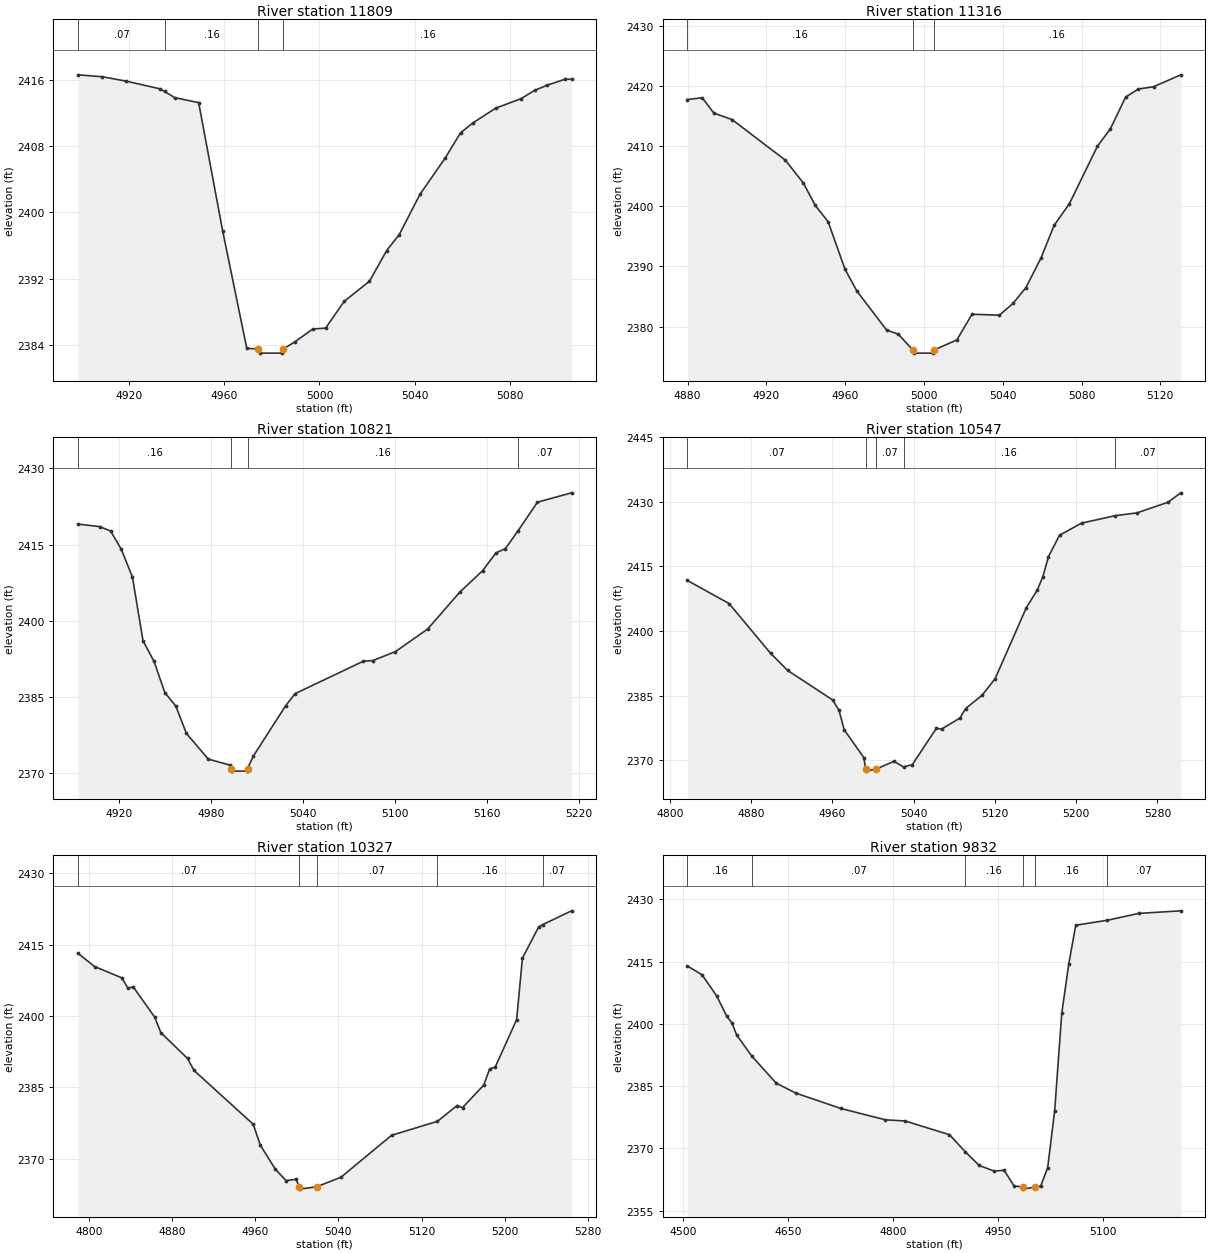
Type RM Length L Ch R = 1 ,11809   ,493,493,493
BEGIN DESCRIPTION:
Bitter Creek Trib6 22.0
END DESCRIPTION:
XS GIS Cut Line= 3
      1430004.97        6801438.      1430105.15      6801422.94
      1430205.01        6801388.
#Sta/Elev= 30
  4898.7 2416.62  4908.8 2416.39    4919 2415.85  4933.2 2414.92    4935 2414.61
  4939.2 2413.87  4949.3 2413.26  4959.4 2397.73  4969.5 2383.58  4974.4  2383.5
  4974.9    2383  4984.3    2383  4984.8  2383.5  4989.7 2384.37  4997.2 2385.91
  5002.6 2386.03  5010.4 2389.26    5021 2391.69  5028.2 2395.39  5033.5 2397.33
  5042.2 2402.19  5052.8 2406.58  5059.2 2409.61  5064.5 2410.83    5074  2412.6
  5084.6 2413.74  5090.3 2414.74  5095.6 2415.37  5103.1 2416.09  5105.8 2416.09
#Mann= 4 ,-1 , 0
  4898.7     .07       0    4935     .16       0  4974.4     .07       0
  4984.8     .16       0
Bank Sta=4974.4,4984.8
XS Rating Curve= 0 ,0
Exp/Cntr=0.3,0.1

Type RM Length L Ch R = 1 ,11316   ,495,495,495
BEGIN DESCRIPTION:
Bitter Creek Trib6 21.0
END DESCRIPTION:
XS GIS Cut Line= 3
      1430254.99        6801888.      1430355.87      6801822.64
      1430455.04      6801737.97
#Sta/Elev= 30
  4879.8 2417.75  4887.4 2418.05  4893.3 2415.49  4902.5 2414.43  4929.6 2407.67
  4938.8 2403.84  4944.8 2400.13  4951.3 2397.45  4959.9 2389.54  4965.9 2385.92
    4981 2379.42    4987 2378.72  4994.4 2376.08  4994.9 2375.58  5004.4 2375.58
  5004.9 2376.08  5016.7 2377.77  5024.4 2382.05  5038.3 2381.89  5045.3 2383.88
  5051.8 2386.49  5059.5 2391.45  5066.1 2396.83  5073.8  2400.4  5088.1 2409.99
  5094.7  2412.9  5102.4 2418.16  5108.9  2419.5  5116.6 2419.88  5130.4 2421.86
#Mann= 3 ,-1 , 0
  4879.8     .16       0  4994.4     .07       0  5004.9     .16       0
Bank Sta=4994.4,5004.9
XS Rating Curve= 0 ,0
Exp/Cntr=0.3,0.1

Type RM Length L Ch R = 1 ,10821   ,274,274,274
BEGIN DESCRIPTION:
Bitter Creek Trib6 20.0
END DESCRIPTION:
XS GIS Cut Line= 3
        1430655.        6802188.       1430731.8      6802114.36
      1430854.98      6801938.03
#Sta/Elev= 30
  4893.6 2419.03  4907.6 2418.54  4914.8 2417.67  4921.8 2414.05    4929 2408.61
  4935.9 2396.09  4943.1 2392.01  4950.1 2385.91  4957.3 2383.21  4964.2 2377.86
  4978.4 2372.82  4992.5 2371.64  4993.5 2370.95    4994 2370.45  5003.5 2370.45
    5004 2370.95  5007.8 2373.42  5028.9 2383.34    5035 2385.69  5079.5 2392.07
  5085.6 2392.19  5100.4 2393.96  5121.4 2398.41  5142.3 2405.65  5157.1 2409.85
  5165.9 2413.38    5172  2414.2    5180 2417.61  5192.9 2423.34  5215.1 2425.18
#Mann= 4 ,-1 , 0
  4893.6     .16       0  4993.5     .07       0    5004     .16       0
    5180     .07       0
Bank Sta=4993.5,5004
XS Rating Curve= 0 ,0
Exp/Cntr=0.3,0.1

Type RM Length L Ch R = 1 ,10547   ,220,220,220
BEGIN DESCRIPTION:
Bitter Creek Trib6 4305
END DESCRIPTION:
XS GIS Cut Line= 3
      1430764.74      6802313.01      1430943.76      6802276.54
      1431063.81      6801998.45
#Sta/Elev= 30
  4817.3 2411.76  4858.4  2406.4  4899.2 2394.86    4916 2390.88  4960.4 2383.99
  4966.6  2381.6  4971.7 2377.08  4991.1  2370.6  4992.8 2367.98  4993.3 2367.48
  5003.3 2367.98  5020.7 2369.75  5030.1 2368.45  5038.8    2369  5062.3 2377.38
  5067.7 2377.27  5085.6  2379.8  5091.2 2382.02  5107.3 2385.07  5120.2 2388.92
  5150.9  2405.4  5161.7 2409.54  5167.2 2412.59  5172.7 2417.25  5183.6 2422.26
  5205.4 2425.07  5238.1 2426.78  5259.8 2427.44  5290.2  2429.9  5302.9  2432.1
#Mann= 5 ,-1 , 0
  4817.3     .07       0  4992.8     .07       0  5003.3     .07       0
  5030.1     .16       0  5238.1     .07       0
Bank Sta=4992.8,5003.3
XS Rating Curve= 0 ,0
Exp/Cntr=0.3,0.1

Type RM Length L Ch R = 1 ,10327   ,495,495,495
BEGIN DESCRIPTION:
Bitter Creek Trib6 19.0
END DESCRIPTION:
XS GIS Cut Line= 3
      1430754.98      6802387.99      1430954.75       6802453.4
      1431205.03      6802538.01
#Sta/Elev= 30
  4789.8 2413.14  4805.7 2410.38  4831.9 2408.01  4837.6 2405.88  4842.9  2406.1
  4863.5 2399.74  4869.4  2396.5    4895  2391.1  4901.3 2388.57  4958.2 2377.28
    4965 2372.88  4979.2 2367.93  4989.7 2365.45  4999.4 2365.74  5002.3 2364.17
  5002.8 2363.67  5019.3 2364.17  5042.5 2366.16  5091.2 2374.97  5135.3  2377.9
  5154.1 2381.21  5159.4 2380.78  5179.7 2385.48  5185.5  2388.9  5190.8 2389.27
  5211.4 2399.24    5217 2412.16  5232.5 2418.67  5236.3 2419.17  5264.2 2422.08
#Mann= 5 ,-1 , 0
  4789.8     .07       0  5002.3     .07       0  5019.3     .07       0
  5135.3     .16       0  5236.3     .07       0
Bank Sta=5002.3,5019.3
XS Rating Curve= 0 ,0
Exp/Cntr=0.3,0.1

Type RM Length L Ch R = 1 ,9832    ,499,499,499
BEGIN DESCRIPTION:
Bitter Creek Trib6 18.0
END DESCRIPTION:
XS GIS Cut Line= 3
        1430655.        6802538.      1430994.19      6802897.71
      1431204.96        6802888.
#Sta/Elev= 30
  4505.6 2413.99  4526.8 2411.83  4547.9 2406.67    4562 2401.84  4569.3 2400.29
  4576.2 2397.33    4598  2392.2  4632.8 2385.71  4661.2  2383.3  4725.1 2379.62
  4788.6 2376.89  4816.9 2376.61  4880.4  2373.3  4902.7 2369.24  4922.9 2365.88
  4944.4 2364.53  4958.5 2364.73  4972.7 2360.96  4985.2 2360.68  4985.7 2360.18
  5002.3 2360.68  5010.8 2360.93  5020.8 2365.35  5030.8  2379.1  5040.9 2402.54
  5050.9 2414.43  5060.9 2423.79  5105.9 2424.98    5151 2426.64    5211 2427.26
#Mann= 6 ,-1 , 0
  4505.6     .16       0    4598     .07       0  4902.7     .16       0
  4985.2     .07       0  5002.3     .16       0  5105.9     .07       0
Bank Sta=4985.2,5002.3
XS Rating Curve= 0 ,0
Exp/Cntr=0.3,0.1

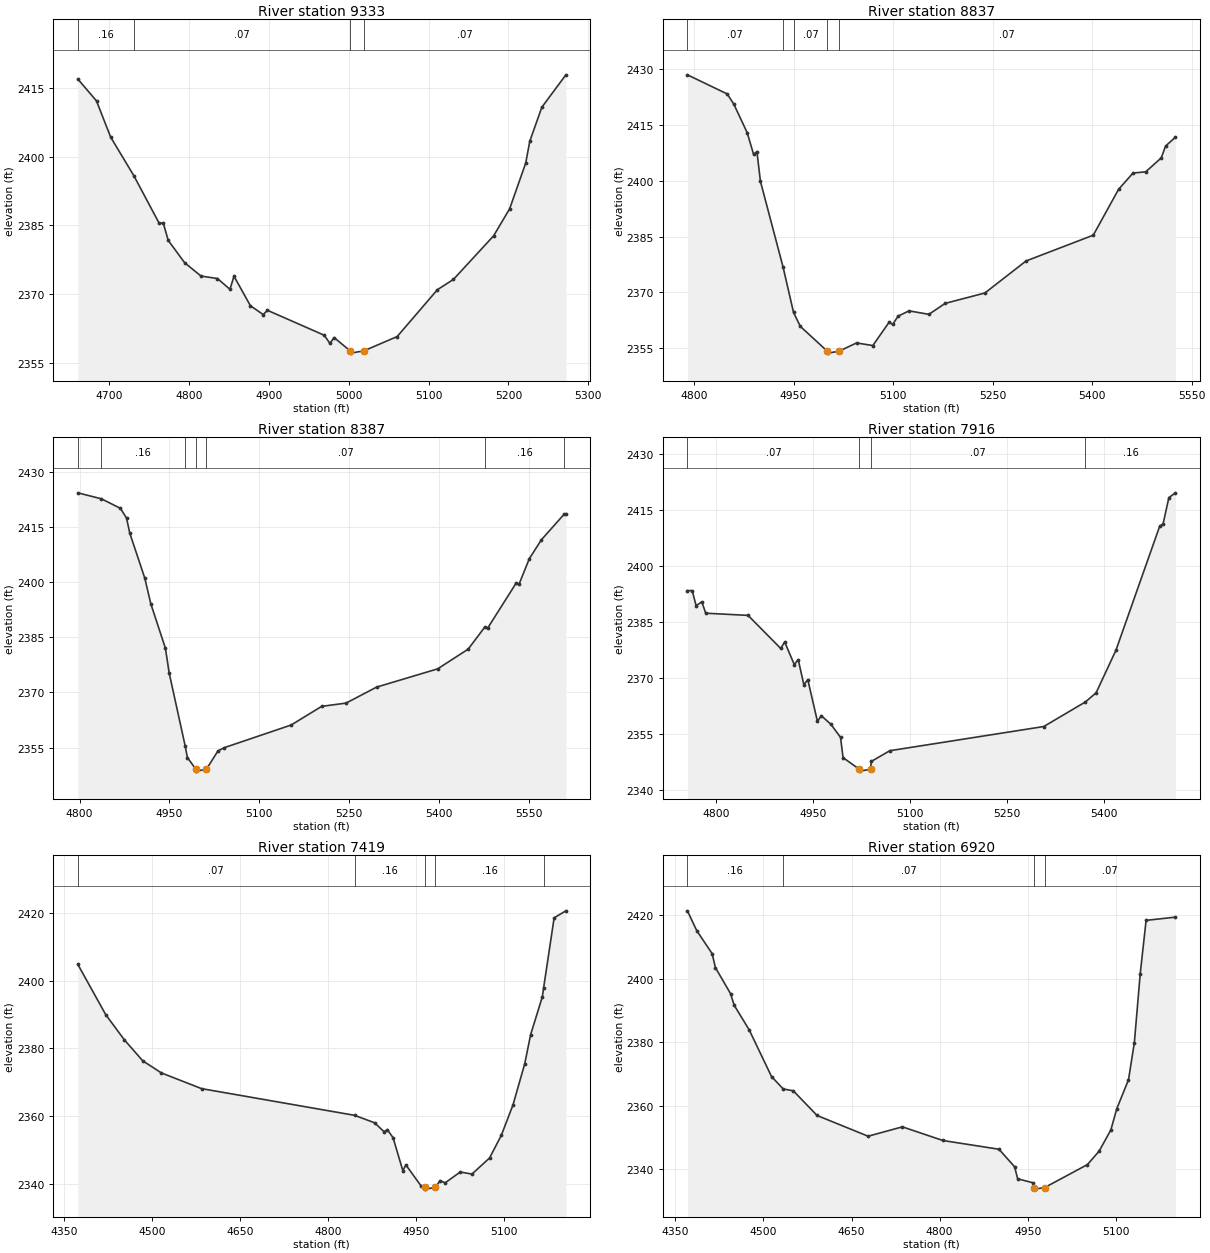
Type RM Length L Ch R = 1 ,9333    ,496,496,496
BEGIN DESCRIPTION:
Bitter Creek Trib6 17.0
END DESCRIPTION:
XS GIS Cut Line= 3
      1430355.02        6803338.      1430684.73      6803257.89
      1430954.96        6803288.
#Sta/Elev= 30
  4660.7 2416.89  4684.1 2412.12  4701.8 2404.24  4730.8 2395.84  4762.5 2385.48
  4767.7 2385.51  4773.9 2381.73  4794.5 2376.85    4815 2373.95  4835.6 2373.41
  4851.2 2371.06  4856.3 2373.91  4876.8 2367.49  4892.9 2365.55  4898.1 2366.49
  4969.4 2361.04  4976.4 2359.26  4981.6 2360.55  5001.7 2357.65  5002.2 2357.15
    5019 2357.65  5060.6 2360.76    5111 2370.97  5131.1 2373.22  5181.4 2382.72
  5201.5 2388.62  5221.6 2398.58  5226.7 2403.33  5241.8 2410.75  5271.9 2417.81
#Mann= 4 ,-1 , 0
  4660.7     .16       0  4730.8     .07       0  5001.7     .07       0
    5019     .07       0
Bank Sta=5001.7,5019
XS Rating Curve= 0 ,0
Exp/Cntr=0.3,0.1

Type RM Length L Ch R = 1 ,8837    ,450,450,450
BEGIN DESCRIPTION:
Bitter Creek Trib6 16.0
END DESCRIPTION:
XS GIS Cut Line= 3
      1430255.01        6803688.      1430464.87      6803677.95
      1430954.96      6803488.02
#Sta/Elev= 30
  4789.9 2428.56    4850  2423.4    4860 2420.61    4880 2412.98  4889.7 2407.12
  4894.7 2407.86    4900 2399.85  4934.2  2376.7  4949.9 2364.53  4960.1 2360.79
  5000.9 2354.08  5001.4 2353.58  5018.2 2354.08  5044.9 2356.33  5069.4 2355.62
    5094 2361.92  5099.4 2361.32  5107.4 2363.53  5123.9 2364.97  5153.9 2364.03
  5178.4 2366.98  5238.3 2369.78  5300.4 2378.41  5401.7 2385.36  5439.8 2397.69
  5461.6  2402.1  5480.8 2402.43  5504.2 2406.19  5510.7 2409.37  5525.6 2411.77
#Mann= 5 ,-1 , 0
  4789.9     .07       0  4934.2     .16       0  4949.9     .07       0
  5000.9     .07       0  5018.2     .07       0
Bank Sta=5000.9,5018.2
XS Rating Curve= 0 ,0
Exp/Cntr=0.3,0.1

Type RM Length L Ch R = 1 ,8387    ,471,471,471
BEGIN DESCRIPTION:
Bitter Creek Trib6 15.0
END DESCRIPTION:
XS GIS Cut Line= 3
      1430204.99        6804038.      1430404.86      6804072.94
      1431005.03      6804188.01
#Sta/Elev= 30
  4797.1 2424.22  4836.5 2422.59  4868.2    2420  4878.3 2417.37  4883.8 2413.25
  4908.8 2401.03  4918.9 2394.03  4943.3 2381.93  4949.4  2375.3  4976.3 2355.33
  4979.8 2352.28  4994.1 2349.09  4994.6 2348.59  5011.5 2349.09  5030.7 2354.04
  5040.9 2354.94  5152.9 2361.12  5203.8 2366.19  5244.5 2367.08  5295.4 2371.42
  5397.2 2376.38  5448.2 2381.75  5475.6 2387.68    5481 2387.54    5528 2399.65
  5533.1 2399.43    5550 2406.28  5570.3 2411.47  5608.3 2418.42  5611.1 2418.46
#Mann= 7 ,-1 , 0
  4797.1     .07       0  4836.5     .16       0  4976.3     .07       0
  4994.1     .07       0  5011.5     .07       0  5475.6     .16       0
  5608.3     .07       0
Bank Sta=4994.1,5011.5
XS Rating Curve= 0 ,0
Exp/Cntr=0.3,0.1

Type RM Length L Ch R = 1 ,7916    ,497,497,497
BEGIN DESCRIPTION:
Bitter Creek Trib6 14.0
END DESCRIPTION:
XS GIS Cut Line= 3
      1430155.01      6804388.01      1430356.08      6804527.46
      1430854.99        6804638.
#Sta/Elev= 30
  4755.3 2393.35  4762.7 2393.37  4768.8 2389.32  4777.6 2390.37  4783.7 2387.32
  4849.2 2386.74  4899.8 2377.89  4905.9 2379.63  4920.8 2373.57  4926.9 2374.89
  4935.6 2368.21  4941.7 2369.55  4956.6 2358.41  4962.7 2359.89  4977.5 2357.61
  4992.4 2354.11  4996.3  2348.7  5021.5 2345.58    5022 2345.08  5038.9 2345.58
  5039.9 2347.66  5068.7 2350.54  5307.1 2357.01  5371.5 2363.58  5388.1 2366.02
  5418.8  2377.4  5486.7 2410.65  5491.8 2411.19  5500.8 2418.24    5511 2419.52
#Mann= 4 ,-1 , 0
  4755.3     .07       0  5021.5     .07       0  5038.9     .07       0
  5371.5     .16       0
Bank Sta=5021.5,5038.9
XS Rating Curve= 0 ,0
Exp/Cntr=0.3,0.1

Type RM Length L Ch R = 1 ,7419    ,499,499,499
BEGIN DESCRIPTION:
Bitter Creek Trib6 13.0
END DESCRIPTION:
XS GIS Cut Line= 3
      1430005.04      6804738.01      1430599.46      6804935.58
      1430805.05        6804938.
#Sta/Elev= 30
  4373.6  2404.8  4421.1 2389.98  4452.7 2382.56  4484.4  2376.3    4516 2372.75
  4584.6  2368.1  4845.4 2360.22  4879.4 2358.02  4895.9 2355.34  4901.2    2356
    4911 2353.61  4927.6  2343.9  4932.9 2345.57  4959.3 2339.22  4965.4 2338.92
  4965.9 2338.42  4983.1 2338.92  4990.9 2340.86    5000  2340.3  5025.5 2343.48
  5045.5 2342.87  5075.5 2347.62  5095.5 2354.29  5115.5 2363.32  5135.5 2375.47
  5145.5 2384.04  5165.5 2395.24  5167.6  2397.8  5185.6 2418.56  5205.6 2420.62
#Mann= 5 ,-1 , 0
  4373.6     .07       0  4845.4     .16       0  4965.4     .07       0
  4983.1     .16       0  5167.6     .07       0
Bank Sta=4965.4,4983.1
XS Rating Curve= 0 ,0
Exp/Cntr=0.3,0.1

Type RM Length L Ch R = 1 ,6920    ,498,498,498
BEGIN DESCRIPTION:
Bitter Creek Trib6 12.0
END DESCRIPTION:
XS GIS Cut Line= 3
      1429905.04      6805138.01      1430503.35      6805334.01
      1430705.01        6805338.
#Sta/Elev= 30
  4370.4 2421.47  4386.3 2415.22  4412.5 2407.98  4418.1 2403.56    4444 2395.31
    4450 2391.71  4475.6 2383.93  4513.7 2369.19  4533.6 2365.28  4550.8 2364.69
  4591.3 2356.91  4678.2 2350.37  4736.6 2353.33  4805.5 2349.02  4901.1 2346.26
  4927.7 2340.74  4932.9 2336.94  4959.5 2335.66  4961.3 2334.18  4961.8 2333.68
    4979 2334.18  5051.7 2341.42  5071.7 2345.66  5091.7 2352.38  5101.7 2359.01
  5121.7 2368.18  5131.7  2379.9  5141.7 2401.68  5151.7 2418.46  5201.7 2419.48
#Mann= 4 ,-1 , 0
  4370.4     .16       0  4533.6     .07       0  4961.3     .07       0
    4979     .07       0
Bank Sta=4961.3,4979
XS Rating Curve= 0 ,0
Exp/Cntr=0.3,0.1

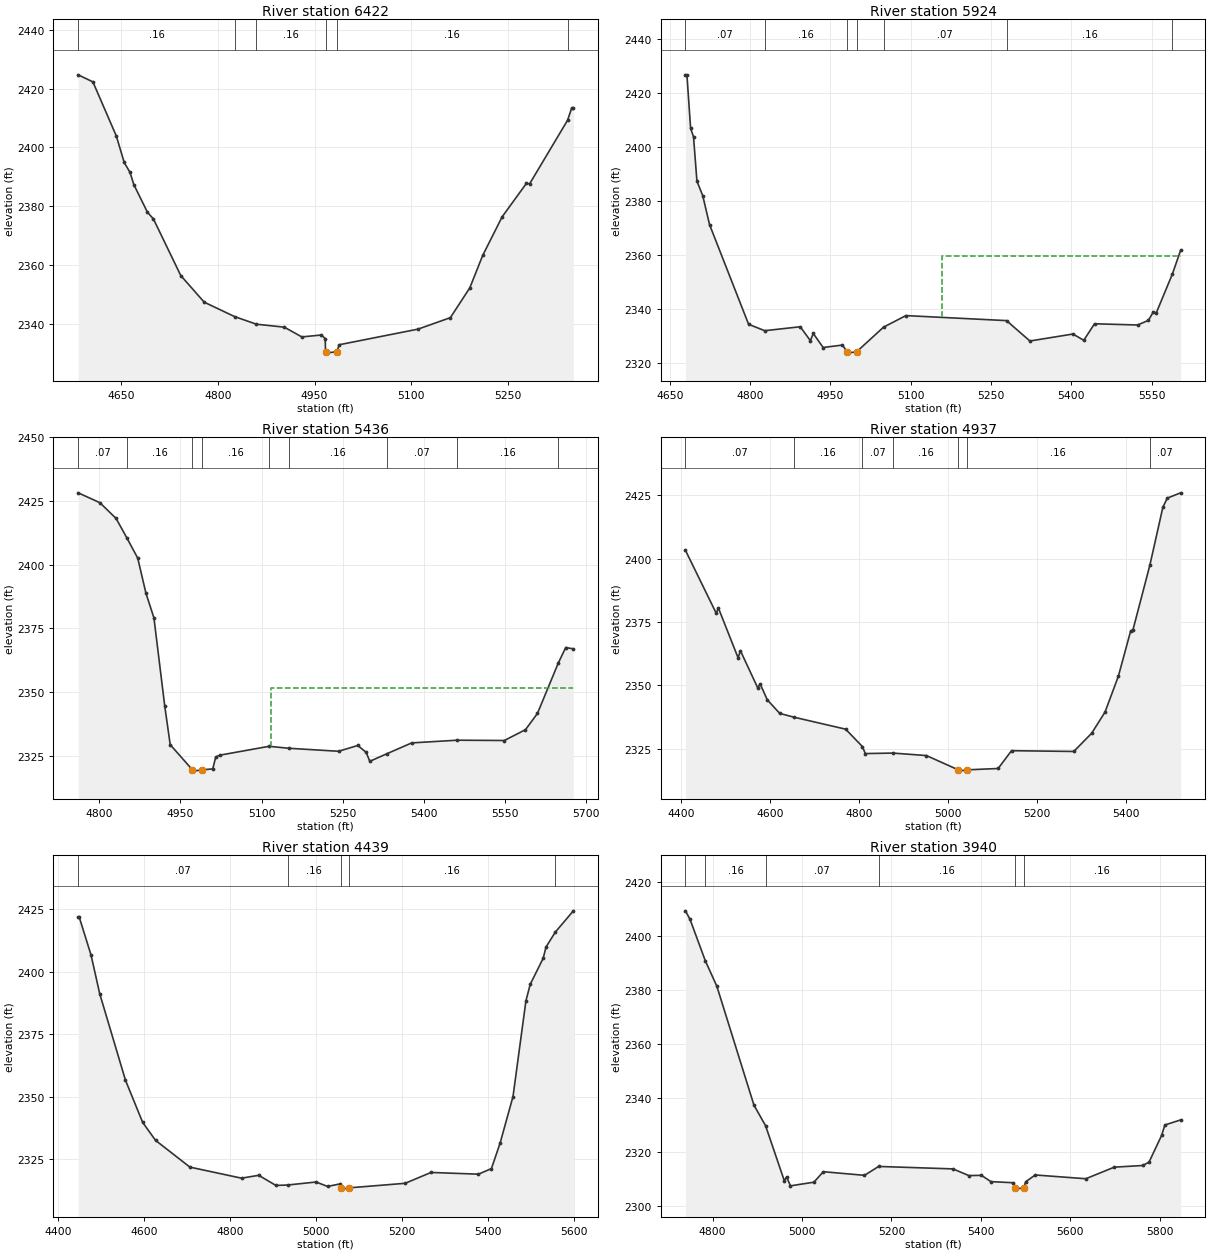
Type RM Length L Ch R = 1 ,6422    ,498,498,498
BEGIN DESCRIPTION:
Bitter Creek Trib6 11.0
END DESCRIPTION:
XS GIS Cut Line= 3
      1429804.99      6805387.99        1430155.        6805613.
      1430505.01        6805638.
#Sta/Elev= 30
  4583.9  2424.7  4606.7  2422.3    4643 2403.87  4655.2 2394.86  4664.2 2391.48
  4670.1 2387.33  4691.2 2377.91  4700.5 2375.62  4742.8 2356.37  4779.1  2347.3
  4826.2 2342.39  4859.9  2339.8  4903.2 2338.79  4930.3 2335.47  4960.7 2336.12
  4966.6 2334.88    4967 2330.45  4967.5 2329.95  4984.7 2330.45  4988.1  2332.8
  5110.3 2338.12  5160.4 2342.03  5190.5 2352.17  5210.5 2363.22  5240.6 2376.36
  5278.2 2387.75  5283.2  2387.6  5341.9 2409.22  5348.4 2413.45  5350.9 2413.45
#Mann= 6 ,-1 , 0
  4583.9     .16       0  4826.2     .07       0  4859.9     .16       0
    4967     .07       0  4984.7     .16       0  5341.9     .07       0
Bank Sta=4967,4984.7
XS Rating Curve= 0 ,0
Exp/Cntr=0.3,0.1

Type RM Length L Ch R = 1 ,5924    ,488,488,488
BEGIN DESCRIPTION:
Bitter Creek Trib6 10.0
END DESCRIPTION:
XS GIS Cut Line= 3
        1429555.        6806088.      1429854.12      6805972.63
      1430454.98        6806038.
#Sta/Elev= 30
  4679.4  2426.8  4682.1  2426.8    4689 2406.99  4694.4 2403.89  4700.8 2387.44
  4711.6 2382.12  4724.4 2371.35  4797.3 2334.49  4827.4 2332.12  4893.8 2333.58
  4912.7 2328.43  4918.1 2331.09  4936.6  2325.9  4972.7 2326.81  4981.3 2324.32
  4981.8 2323.82  4999.1 2324.32  5049.4 2333.43  5091.1 2337.71  5279.1 2335.85
  5322.8 2328.31  5403.2 2330.89  5423.4 2328.57  5443.5 2334.68    5524 2334.23
  5544.1 2335.93  5553.6 2339.14  5558.7 2338.64  5588.8 2353.01  5604.4 2361.92
#Mann= 7 ,-1 , 0
  4679.4     .07       0  4827.4     .16       0  4981.3     .07       0
  4999.1     .16       0  5049.4     .07       0  5279.1     .16       0
  5588.8     .07       0
#XS Ineff= 2 , 0
                         5157.88         2359.84
Permanent Ineff=
       F       F
Bank Sta=4981.3,4999.1
XS Rating Curve= 0 ,0
Exp/Cntr=0.3,0.1

Type RM Length L Ch R = 1 ,5436    ,499,499,499
BEGIN DESCRIPTION:
Bitter Creek Trib6 9.0
END DESCRIPTION:
XS GIS Cut Line= 3
      1429654.98        6806388.      1429893.89      6806378.47
      1430504.97      6806088.01
#Sta/Elev= 30
  4760.9 2428.24  4800.9 2424.38    4831 2418.18  4851.3 2410.39    4871  2402.6
  4886.2 2388.82    4901  2379.1    4921 2344.48  4931.1 2329.31  4972.2 2319.41
  4972.7 2318.91    4990 2319.41  5009.8 2319.79  5015.3 2324.48  5023.4  2325.2
  5113.9 2328.66  5150.2 2327.89  5242.5 2326.71    5278 2328.99  5293.5 2326.27
  5300.2 2322.76  5331.1 2325.68  5377.7    2330  5461.9 2331.06  5548.9 2330.94
  5588.1  2335.2  5610.2 2341.58  5648.8  2361.4  5662.5 2367.47  5676.6 2366.95
#Mann= 9 ,-1 , 0
  4760.9     .07       0  4851.3     .16       0  4972.2     .07       0
    4990     .16       0  5113.9     .07       0  5150.2     .16       0
  5331.1     .07       0  5461.9     .16       0  5648.8     .07       0
#XS Ineff= 2 , 0
                         5117.63         2351.49
Permanent Ineff=
       F       F
Bank Sta=4972.2,4990
XS Rating Curve= 0 ,0
Exp/Cntr=0.3,0.1

Type RM Length L Ch R = 1 ,4937    ,498,498,498
BEGIN DESCRIPTION:
Bitter Creek Trib6 8.0
END DESCRIPTION:
XS GIS Cut Line= 3
      1429705.03      6806737.99      1430282.49      6806614.08
      1430805.04        6806638.
#Sta/Elev= 30
  4409.4 2403.31  4478.4 2378.53  4483.5 2380.51  4527.8 2360.83  4532.9 2363.69
    4572 2348.94  4577.2 2350.57  4593.5 2344.23  4621.4 2338.89  4653.5 2337.39
  4769.6 2332.66  4807.2 2325.81  4813.9 2323.02  4876.1 2323.21  4951.4 2322.23
    5023 2316.58  5023.5 2316.08  5042.1 2316.58  5112.6 2317.12  5142.7 2324.16
  5282.8 2323.85  5322.9 2331.04  5352.9 2339.38  5382.9 2353.53  5410.8 2371.55
  5415.8 2371.89  5453.9  2397.5    5483 2420.29    5493 2423.96  5523.1 2426.05
#Mann= 7 ,-1 , 0
  4409.4     .07       0  4653.5     .16       0  4807.2     .07       0
  4876.1     .16       0    5023     .07       0  5042.1     .16       0
  5453.9     .07       0
Bank Sta=5023,5042.1
XS Rating Curve= 0 ,0
Exp/Cntr=0.3,0.1

Type RM Length L Ch R = 1 ,4439    ,499,499,499
BEGIN DESCRIPTION:
Bitter Creek Trib6 7.0
END DESCRIPTION:
XS GIS Cut Line= 3
      1429654.96        6807038.      1430208.56      6807039.47
      1430804.99        6807088.
#Sta/Elev= 30
  4446.4 2421.78  4448.9 2421.78  4476.4 2406.61  4496.4 2391.25  4556.4 2356.61
  4596.4 2339.74  4626.4 2332.55  4706.4 2321.85  4826.4 2317.43  4866.4 2318.58
  4906.4 2314.53  4933.4 2314.69    5000  2315.9  5026.5 2314.12  5056.6 2315.17
  5057.1 2313.55  5057.6 2313.05  5076.3 2313.55  5207.1 2315.38  5267.3 2319.72
  5377.7 2319.03  5407.8 2321.26  5427.9 2331.41    5458 2350.07  5488.1 2388.37
  5498.1 2394.95  5528.2 2405.35    5535 2409.92  5556.7 2415.86  5598.4 2424.32
#Mann= 5 ,-1 , 0
  4446.4     .07       0  4933.4     .16       0  5057.1     .07       0
  5076.3     .16       0  5556.7     .07       0
Bank Sta=5057.1,5076.3
XS Rating Curve= 0 ,0
Exp/Cntr=0.3,0.1

Type RM Length L Ch R = 1 ,3940    ,497,497,497
BEGIN DESCRIPTION:
Bitter Creek Trib6 6.0
END DESCRIPTION:
XS GIS Cut Line= 3
      1429655.03      6807387.99      1429910.34      6807335.26
        1430505.        6807938.
#Sta/Elev= 30
  4739.3  2409.3  4749.5 2406.12  4783.6 2390.81  4809.5 2381.32  4892.4 2337.28
  4918.5 2329.61  4960.3 2309.24  4965.4 2310.65  4974.1 2307.35  5026.5  2308.7
  5047.6 2312.59  5139.6 2311.24  5171.3 2314.54  5337.6 2313.63  5372.9 2311.15
  5401.2 2311.24  5422.5 2308.91  5471.9  2308.5  5476.5 2306.63    5477 2306.13
  5495.7 2306.63  5500.2 2308.86  5521.5 2311.38  5634.6 2309.98  5698.2 2314.27
  5761.9 2314.89    5776 2316.15  5804.3  2326.1  5811.3 2329.91  5846.7 2331.79
#Mann= 6 ,-1 , 0
  4739.3     .07       0  4783.6     .16       0  4918.5     .07       0
  5171.3     .16       0  5476.5     .07       0  5495.7     .16       0
Bank Sta=5476.5,5495.7
XS Rating Curve= 0 ,0
Exp/Cntr=0.3,0.1

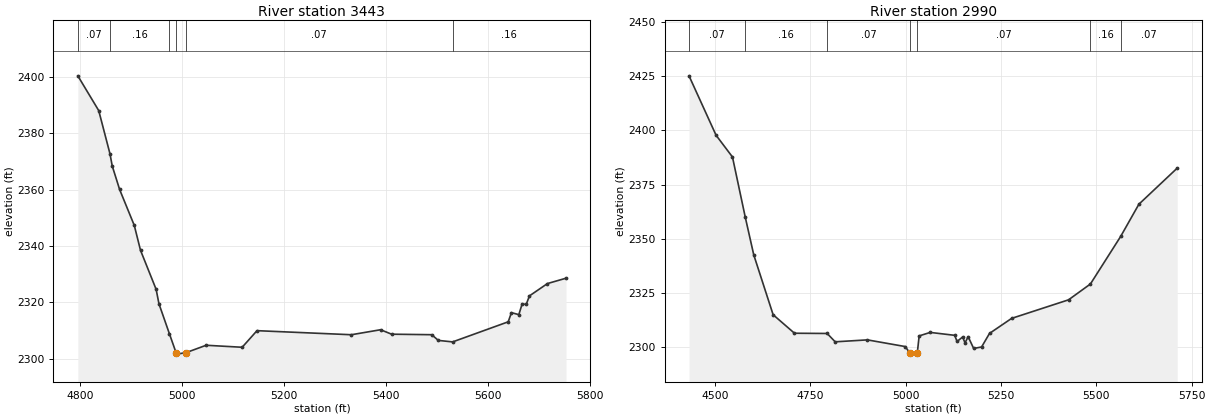
Type RM Length L Ch R = 1 ,3443    ,453,453,453
BEGIN DESCRIPTION:
Bitter Creek Trib6 5.0
END DESCRIPTION:
XS GIS Cut Line= 3
        1429605.        6807738.      1429804.91      6807782.96
      1430404.99      6808237.99
#Sta/Elev= 30
  4795.1 2400.27  4836.1 2387.96  4858.2 2372.65  4862.6 2368.35  4877.1 2360.01
  4905.9 2347.28  4918.1 2338.47  4948.8 2324.62  4954.3 2319.52  4974.9 2308.86
  4987.9 2302.19  4988.4 2301.69  5007.1 2302.19  5046.9 2304.83  5117.6 2304.12
  5146.7    2310  5331.9 2308.56  5389.2 2310.33  5410.9 2308.75  5489.6 2308.57
  5502.5 2306.55  5530.6 2306.02  5639.7 2313.14    5646 2316.38  5660.5 2315.68
  5666.8 2319.35  5675.1 2319.38  5681.4 2322.33  5716.7 2326.69  5753.1 2328.58
#Mann= 6 ,-1 , 0
  4795.1     .07       0  4858.2     .16       0  4974.9     .07       0
  4987.9     .07       0  5007.1     .07       0  5530.6     .16       0
Bank Sta=4987.9,5007.1
XS Rating Curve= 0 ,0
Exp/Cntr=0.3,0.1

Type RM Length L Ch R = 1 ,2990    ,599,599,599
BEGIN DESCRIPTION:
Bitter Creek Trib6 4.0
END DESCRIPTION:
XS GIS Cut Line= 3
      1429454.98      6807837.98      1429892.46      6808201.35
      1430454.98      6808637.99
#Sta/Elev= 30
  4431.3 2425.06  4502.3  2397.7  4545.3 2387.69  4578.9 2359.97  4601.2 2342.59
    4652 2315.05    4708 2306.53  4793.7 2306.42  4814.8 2302.58  4899.4 2303.47
  4998.4  2300.4    5011 2297.41  5011.5 2296.91  5030.2 2297.41  5035.1  2305.3
  5064.1 2306.91  5128.3 2305.57  5134.6 2302.73  5149.1 2304.79  5155.5 2302.11
  5163.6 2304.95  5178.1 2299.52  5198.9  2300.2  5219.7 2306.45  5277.7 2313.37
    5427 2321.91  5484.4  2329.2  5563.7 2351.08  5611.6 2365.94  5712.1 2382.55
#Mann= 7 ,-1 , 0
  4431.3     .07       0  4578.9     .16       0  4793.7     .07       0
    5011     .07       0  5030.2     .07       0  5484.4     .16       0
  5563.7     .07       0
Bank Sta=5011,5030.2
XS Rating Curve= 0 ,0
Exp/Cntr=0.3,0.1