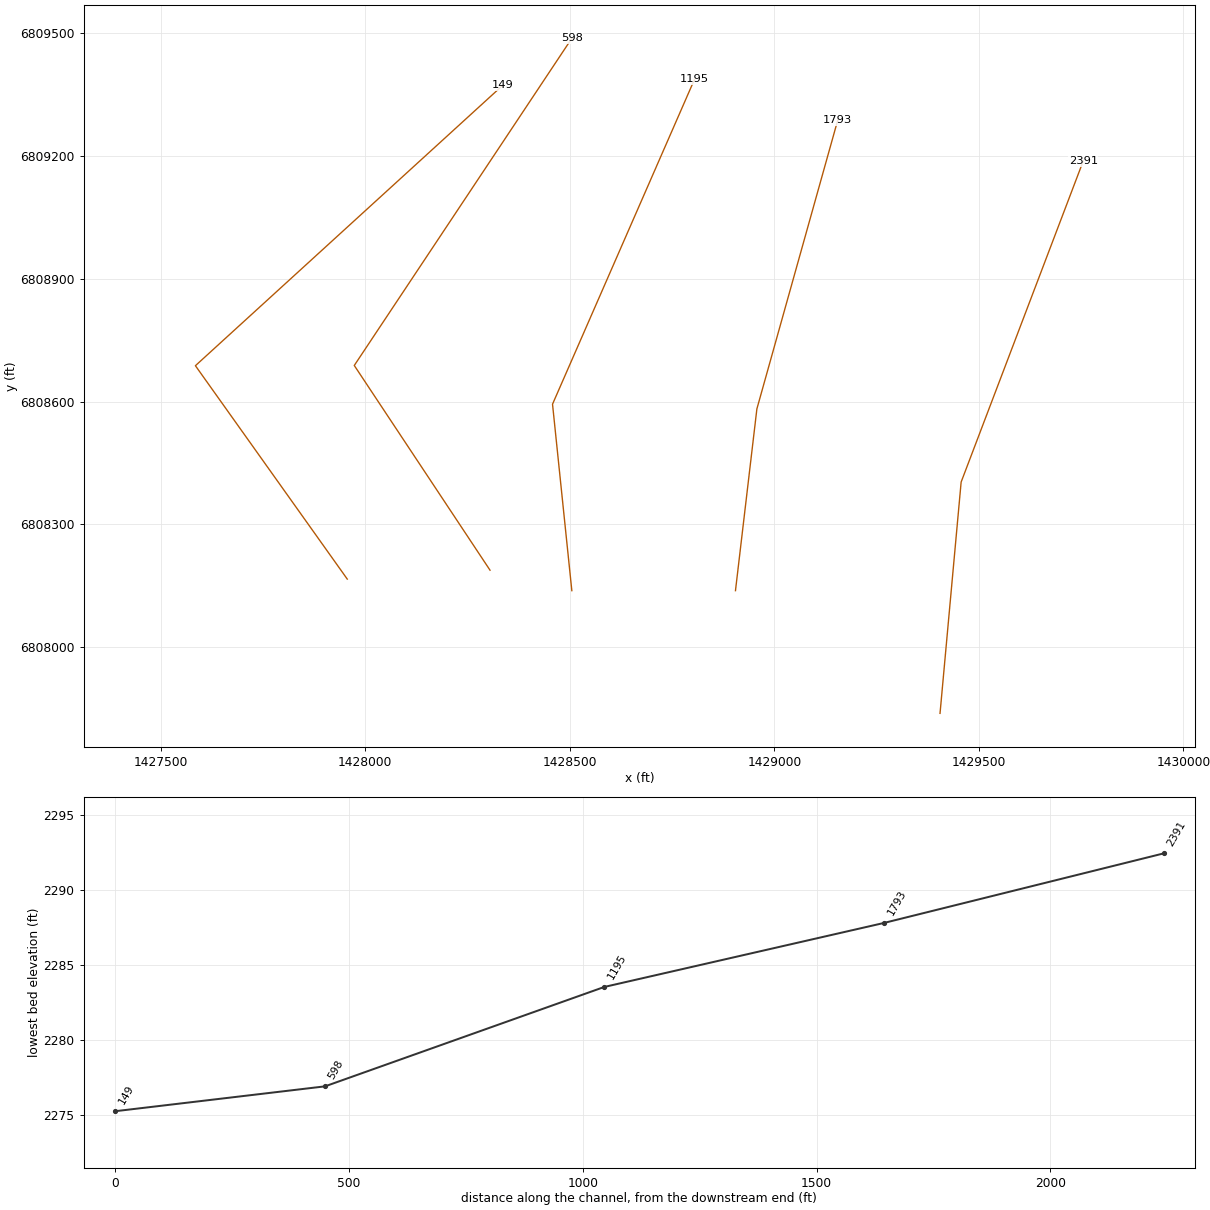
HEC-RAS study Bitter Creek Trib6.prj: Bitter Creek Trib6 Base Level Engineering

--- Bitter Creek Trib6.g01 (geometry) --- (continued)

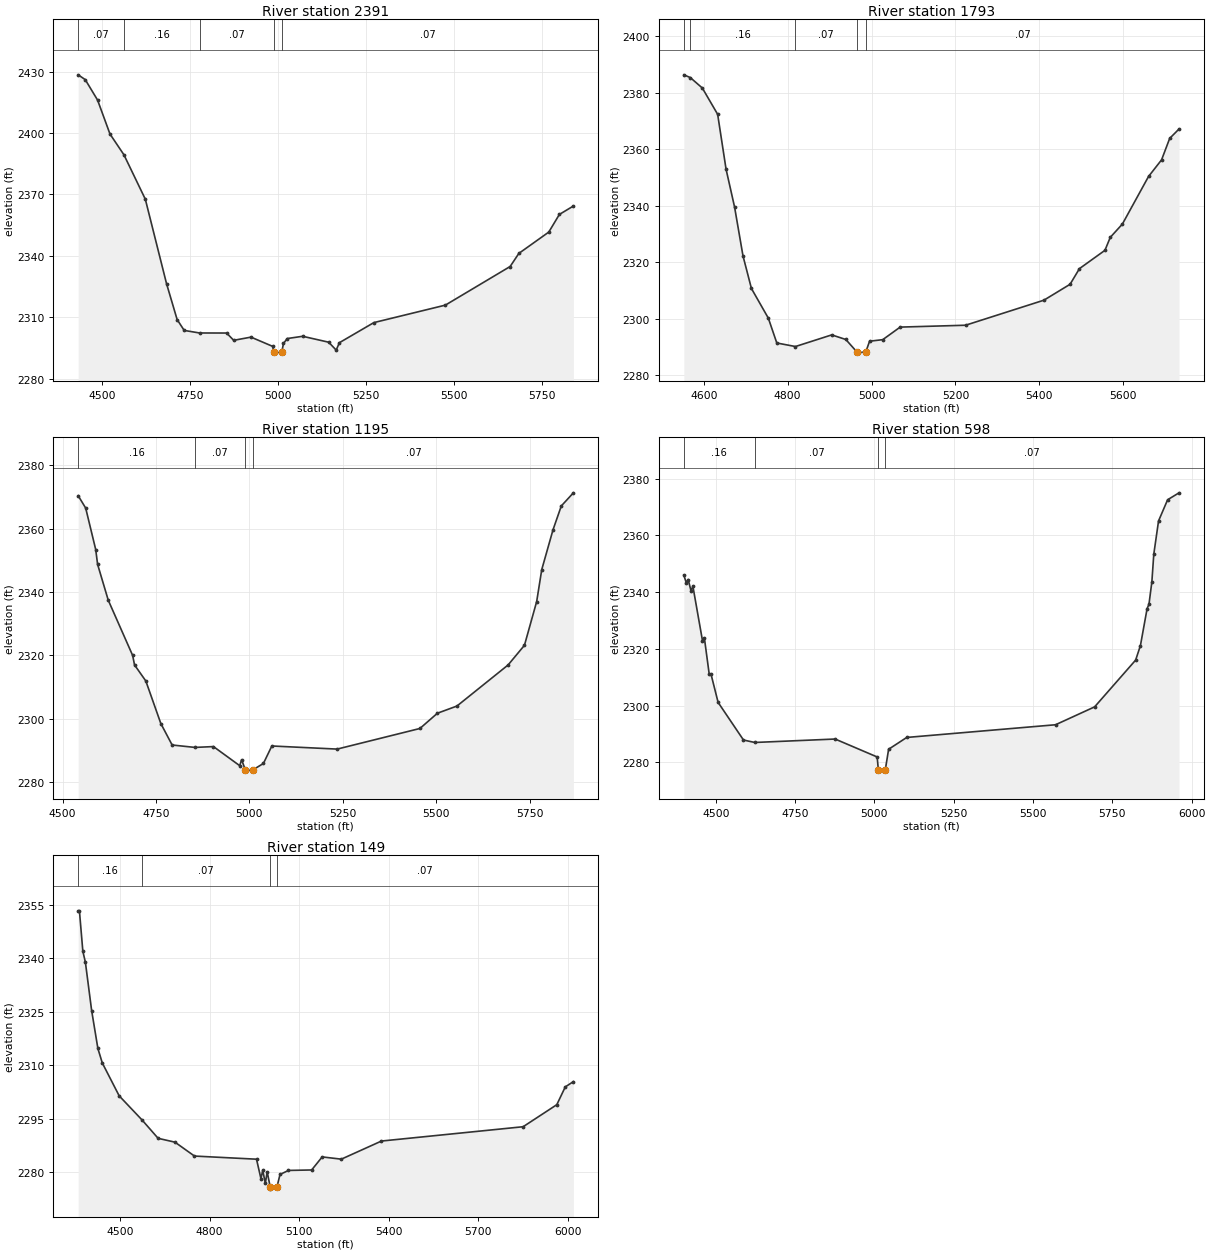
Type RM Length L Ch R = 1 ,2391    ,598,598,598
BEGIN DESCRIPTION:
Bitter Creek Trib6 3.0
END DESCRIPTION:
XS GIS Cut Line= 3
        1429405.      6807837.98       1429456.6      6808403.43
        1429755.        6809188.
#Sta/Elev= 30
  4432.2 2428.45  4452.3  2426.1  4487.3 2416.12  4522.6 2399.51  4562.2 2389.37
    4623 2367.66  4683.3 2326.37  4713.4 2308.82  4733.5 2303.52    4777 2302.27
    4854 2302.24  4874.1 2298.68  4923.3 2300.24  4984.5 2295.75  4988.9 2292.92
  4989.4 2292.42  5010.7 2292.92  5015.6 2297.15  5026.3 2299.55  5070.1 2300.65
    5144 2297.76  5165.4  2293.9  5174.5 2297.52  5272.4 2307.34  5475.6 2315.88
  5659.7 2334.76  5684.5 2341.17  5769.5 2351.59  5799.6 2360.21  5839.4 2364.32
#Mann= 5 ,-1 , 0
  4432.2     .07       0  4562.2     .16       0    4777     .07       0
  4988.9     .07       0  5010.7     .07       0
Bank Sta=4988.9,5010.7
XS Rating Curve= 0 ,0
Exp/Cntr=0.3,0.1

Type RM Length L Ch R = 1 ,1793    ,598,598,598
BEGIN DESCRIPTION:
Bitter Creek Trib6 2.0
END DESCRIPTION:
XS GIS Cut Line= 3
        1428905.      6808137.97      1428957.35      6808582.29
      1429155.01      6809288.03
#Sta/Elev= 30
  4552.6 2386.37  4567.9 2385.41  4596.7 2381.69  4633.2 2372.38  4653.3  2352.9
  4673.5 2339.56  4693.6 2322.23  4713.7 2310.68    4754 2300.17  4774.2 2291.37
  4818.6 2290.12  4905.1 2294.24  4938.7 2292.61  4964.6 2288.28  4965.1 2287.78
  4986.5 2288.28  4995.3    2292  5026.7 2292.55  5068.2    2297    5224 2297.66
  5410.9 2306.54  5473.2 2312.17  5495.5 2317.71  5556.3  2324.2    5569 2328.79
  5597.9 2333.51  5660.2 2350.36  5691.3 2356.26  5710.6 2363.85  5732.9 2367.18
#Mann= 5 ,-1 , 0
  4552.6     .07       0  4567.9     .16       0  4818.6     .07       0
  4964.6     .07       0  4986.5     .07       0
Bank Sta=4964.6,4986.5
XS Rating Curve= 0 ,0
Exp/Cntr=0.3,0.1

Type RM Length L Ch R = 1 ,1195    ,597,597,597
BEGIN DESCRIPTION:
Bitter Creek Trib6 1.0
END DESCRIPTION:
XS GIS Cut Line= 3
        1428505.      6808137.96      1428457.83      6808593.72
      1428804.99      6809387.97
#Sta/Elev= 30
  4541.8 2370.37  4561.9 2366.47  4588.7  2353.4  4593.8 2348.71  4622.3 2337.41
  4687.6 2319.98  4692.6    2317  4722.8 2311.94    4763 2298.51  4793.2 2291.75
  4854.1 2290.99  4903.8 2291.25    4974 2285.23  4979.1 2287.11  4988.7 2284.01
  4989.2 2283.51  5010.6 2284.01  5037.4 2285.92    5060 2291.44  5234.7 2290.46
  5456.2 2296.96    5503 2301.77  5555.3 2304.04  5692.2    2317  5735.9  2323.2
  5768.6    2337  5782.2 2347.08  5812.3 2359.62  5834.5 2367.14  5866.8 2371.28
#Mann= 4 ,-1 , 0
  4541.8     .16       0  4854.1     .07       0  4988.7     .07       0
  5010.6     .07       0
Bank Sta=4988.7,5010.6
XS Rating Curve= 0 ,0
Exp/Cntr=0.3,0.1

Type RM Length L Ch R = 1 ,598     ,449,449,449
BEGIN DESCRIPTION:
Bitter Creek Trib6 0.1
END DESCRIPTION:
XS GIS Cut Line= 3
      1428305.03      6808187.96      1427973.23      6808688.35
      1428504.99      6809487.98
#Sta/Elev= 30
  4399.6 2345.91  4407.2 2343.34  4413.2 2344.41  4422.2 2340.45  4428.2    2342
  4458.3  2322.9  4464.3 2323.84  4479.4  2311.2  4485.4 2310.99  4507.6 2301.11
  4587.6 2287.84  4623.3 2286.98  4876.4 2288.19  5008.9 2281.87  5012.6 2277.38
  5013.1 2276.88  5034.6 2277.38    5045 2284.59  5102.1 2288.75    5571 2293.22
  5694.3 2299.53  5823.5 2316.01  5838.6 2321.12  5859.6 2334.12  5865.6 2335.72
  5874.7 2343.64  5880.7 2353.31  5895.7 2365.05  5924.3 2372.52  5960.3 2374.96
#Mann= 4 ,-1 , 0
  4399.6     .16       0  4623.3     .07       0  5012.6     .07       0
  5034.6     .07       0
Bank Sta=5012.6,5034.6
XS Rating Curve= 0 ,0
Exp/Cntr=0.3,0.1

Type RM Length L Ch R = 1 ,149     ,0,0,0
BEGIN DESCRIPTION:
Bitter Creek Trib6 4273
END DESCRIPTION:
XS GIS Cut Line= 3
      1427956.12      6808166.19      1427584.93       6808687.8
      1428337.04      6809373.99
#Sta/Elev= 30
  4359.8 2353.23    4364 2353.23  4375.4 2341.92    4384 2338.79  4404.9 2325.27
  4425.8 2314.64  4440.6 2310.58  4497.1 2301.37    4574 2294.58  4627.5 2289.46
    4684 2288.38  4749.2 2284.49    4957 2283.61  4971.8 2278.18  4977.9 2280.51
  4986.5 2276.81  4992.7 2280.09  5003.1 2275.72  5003.6 2275.22  5025.1 2275.72
  5035.7 2279.33    5064 2280.46  5141.7 2280.59  5176.9 2284.25    5241 2283.62
  5375.5  2288.7  5849.8 2292.71  5962.6 2298.89    5991 2303.88  6018.1 2305.35
#Mann= 4 ,-1 , 0
  4359.8     .16       0    4574     .07       0  5003.1     .07       0
  5025.1     .07       0
Bank Sta=5003.1,5025.1
XS Rating Curve= 0 ,0
Exp/Cntr=0.3,0.1

Chan Stop Cuts=-1
Use User Specified Reach Order=0
Composite Channel Slope=5