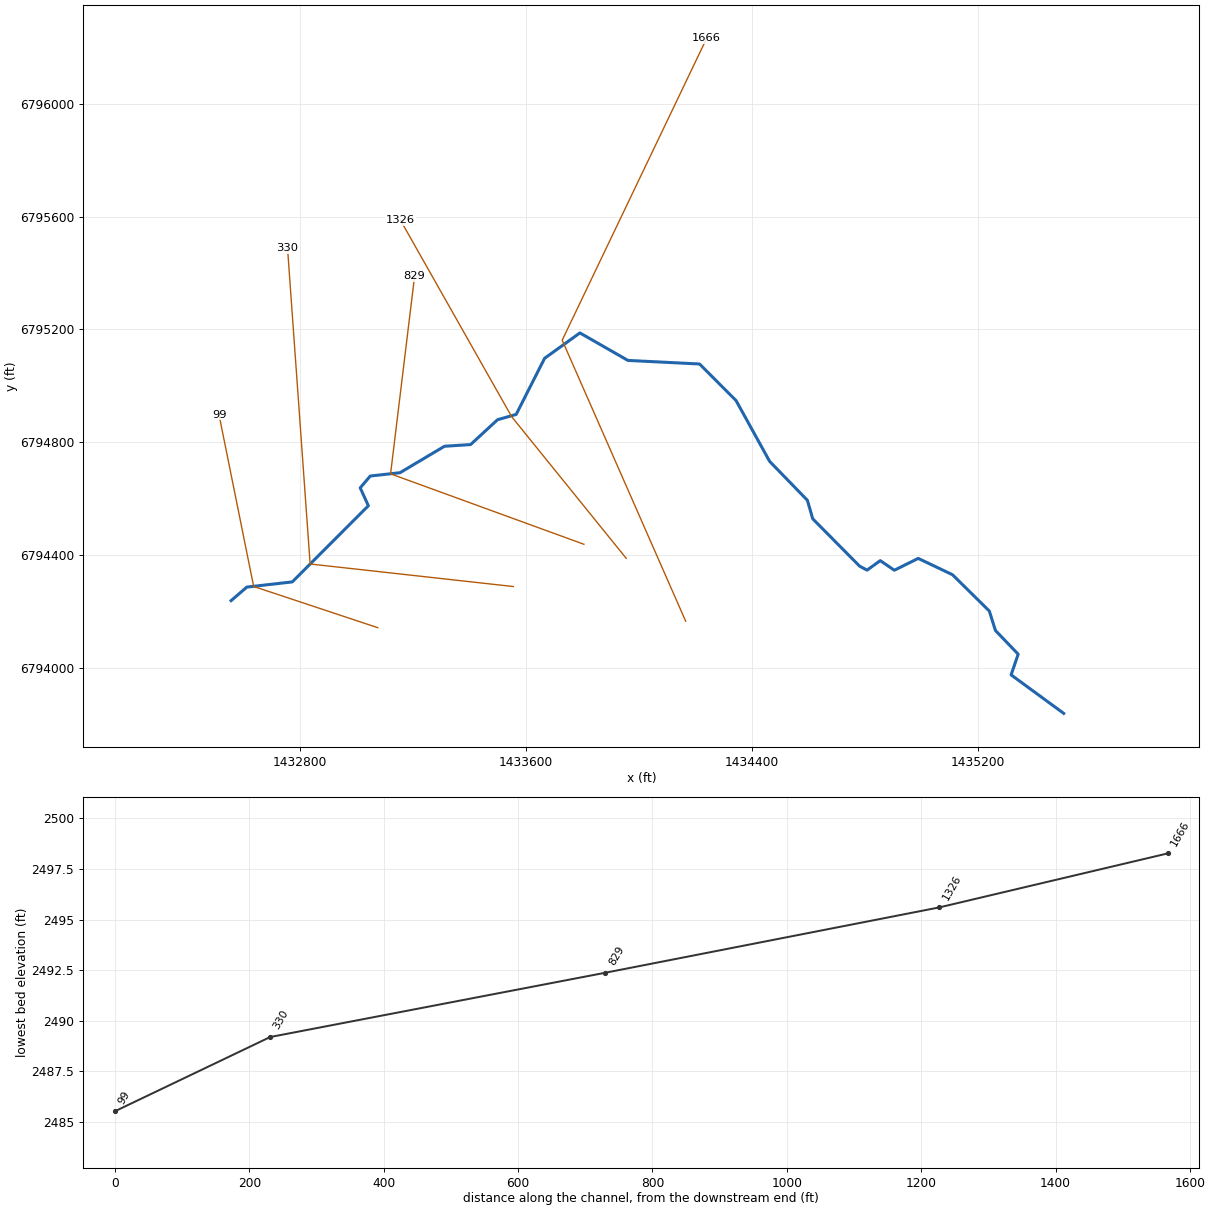
--- Bitter Creek Trib6T1.prj (project) ---

Proj Title=Bitter Creek Trib6T1 Base Level Engineering
Current Plan=p01
Default Exp/Contr=0.3,0.1
English Units
Geom File=g01
Flow File=f01
Plan File=p01
Y Axis Title=Elevation
X Axis Title(PF)=Main Channel Distance
X Axis Title(XS)=Station
BEGIN DESCRIPTION:
Bitter Creek Trib6T1
END DESCRIPTION:
DSS Export Rating Curves= 0
DSS Export Rating Curve Sorted= 0
DSS Export Volume Flow Curves= 0
DXF OffsetX= 0
DXF OffsetY= 0
DXF ScaleX= 1
DXF ScaleY= 10

--- Bitter Creek Trib6T1.p01 (plan) ---

Plan Title=Multiple Run
Short Identifier=Multiple
Geom File=g01
Flow File=f01
Subcritical Flow
K Sum by GR= 0
Std Step Tol= 0.01
Critical Tol= 0.01
Num of Std Step Trials= 20
Max Error Tol= 0.3
Flow Tol Ratio= 0.001
Split Flow NTrial= 30
Split Flow Tol= 0.02
Split Flow Ratio= 0.02
Log Output Level= 0
Friction Slope Method= 1
Unsteady Friction Slope Method= 2
Unsteady Bridges Friction Slope Method= 1
Parabolic Critical Depth
Global Vel Dist=  1 , 1 , 1
Global Log Level= 0
CheckData=True
Encroach Param= -1, 0, 0, 0
BEGIN DESCRIPTION:
Multiple Run
END DESCRIPTION:

--- Bitter Creek Trib6T1.f01 (steady flow) ---

Flow Title=Multiple
Number of Profiles=7
Profile Names=10-year,25-year,50-year,1pct_min,100-year,1pct_plu,500-year
River Rch & RM= Bitter Creek Tri,Reach-1,1666
     158     207     244     143     285     568     393
Boundary for River Rch & Prof#=Bitter Creek Tri,Reach-1,1
Up Type=0
Dn Type=3
Dn Slope=0.005
Boundary for River Rch & Prof#=Bitter Creek Tri,Reach-1,2
Up Type=0
Dn Type=3
Dn Slope=0.005
Boundary for River Rch & Prof#=Bitter Creek Tri,Reach-1,3
Up Type=0
Dn Type=3
Dn Slope=0.005
Boundary for River Rch & Prof#=Bitter Creek Tri,Reach-1,4
Up Type=0
Dn Type=3
Dn Slope=0.005
Boundary for River Rch & Prof#=Bitter Creek Tri,Reach-1,5
Up Type=0
Dn Type=3
Dn Slope=0.005
Boundary for River Rch & Prof#=Bitter Creek Tri,Reach-1,6
Up Type=0
Dn Type=3
Dn Slope=0.005
Boundary for River Rch & Prof#=Bitter Creek Tri,Reach-1,7
Up Type=0
Dn Type=3
Dn Slope=0.005

--- Bitter Creek Trib6T1.g01 (geometry) ---

Geom Title=Existing Conditions

River Reach=Bitter Creek Tri,Reach-1
Reach XY= 30
      1435505.00      6793838.00      1435318.64      6793974.64
      1435343.74      6794047.99      1435263.20      6794131.95
      1435241.37      6794201.21      1435111.06      6794329.86
      1434989.59      6794387.87      1434904.91      6794345.81
      1434855.00      6794379.96      1434808.33      6794346.13
      1434781.67      6794360.51      1434615.78      6794528.32
      1434596.84      6794594.05      1434463.16      6794731.95
      1434344.22      6794947.68      1434214.80      6795077.52
      1433960.93      6795090.24      1433790.88      6795187.83
      1433665.76      6795097.71      1433565.00      6794898.65
      1433498.98      6794879.81      1433403.50      6794791.62
      1433310.97      6794785.67      1433153.41      6794691.83
      1433048.20      6794680.14      1433012.46      6794638.24
      1433041.35      6794574.67      1432771.76      6794304.43
      1432610.79      6794286.09      1432555.00      6794238.00

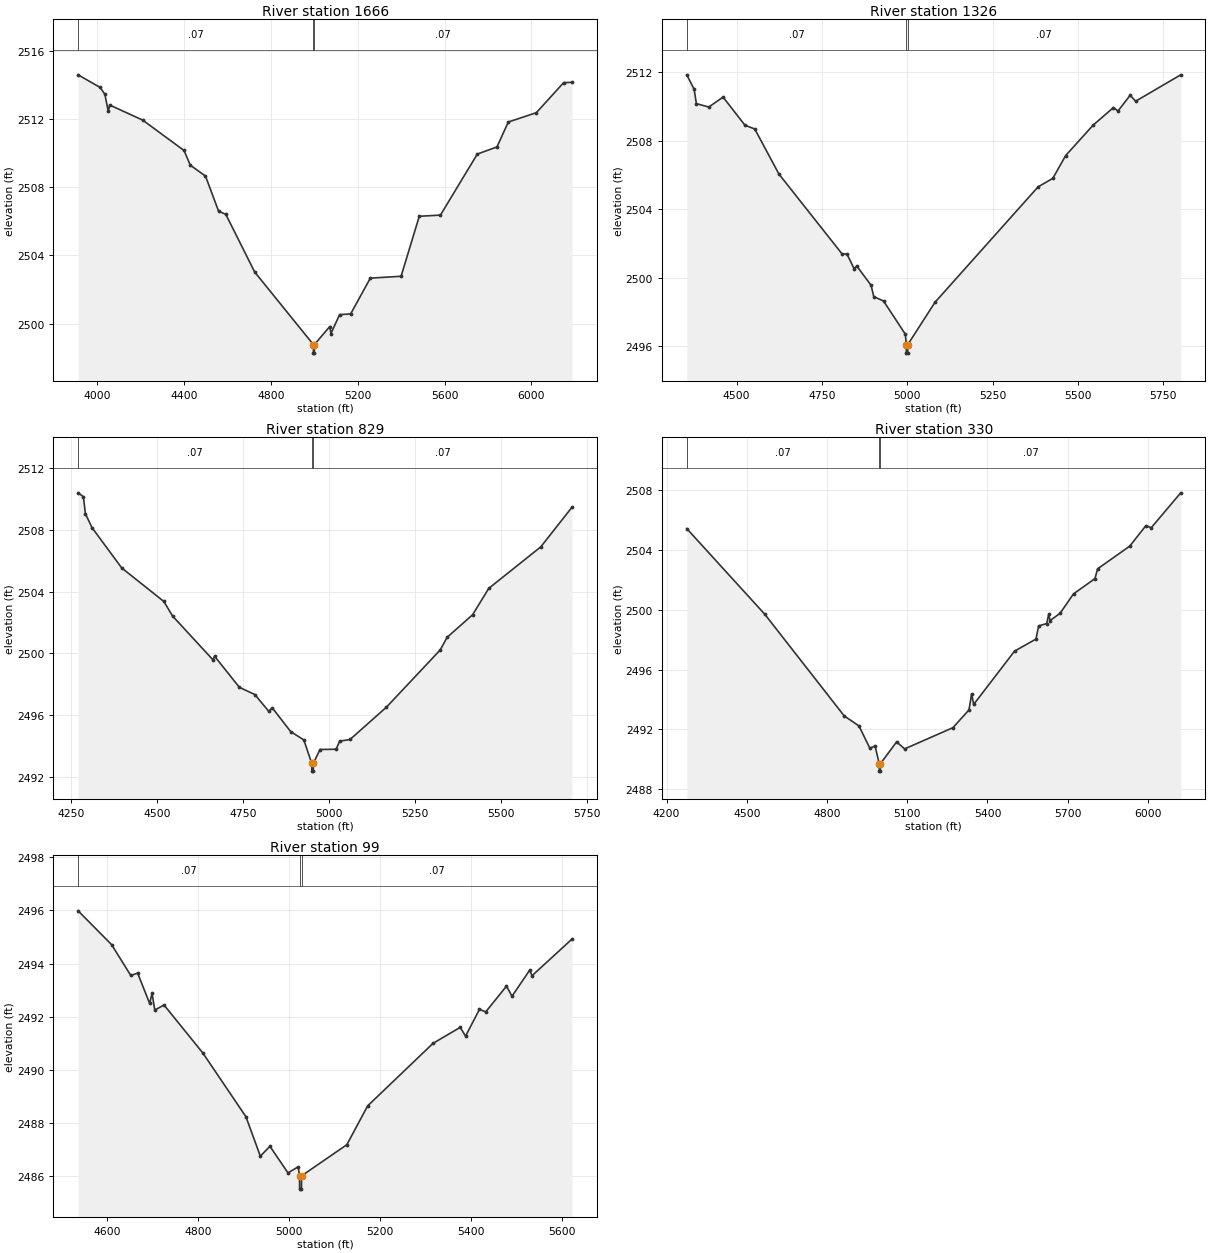
Type RM Length L Ch R = 1,1666,340,340,340
BEGIN DESCRIPTION:
Bitter Creek Trib6T1 3.0
END DESCRIPTION:
XS GIS Cut Line= 3
      1434165.60      6794165.05      1433728.12      6795161.99
      1434239.99      6796232.95
#Sta/Elev= 30
  3911.3 2514.60  4012.8 2513.86  4034.6 2513.46  4050.3 2512.45  4056.5 2512.83
  4209.4 2511.94  4399.3 2510.16  4428.1 2509.30  4498.2 2508.66  4558.8 2506.59
  4591.6 2506.42  4724.8 2503.03  4995.4 2498.77  4995.7 2498.27  4999.6 2498.27
  4999.9 2498.77  5070.8 2499.83  5076.3 2499.42  5116.1 2500.53  5167.0 2500.57
  5257.7 2502.67  5399.4 2502.78  5483.3 2506.30  5580.8 2506.37  5750.6 2509.95
  5841.3 2510.37  5893.3 2511.83  6022.8 2512.38  6148.3 2514.14  6187.0 2514.16
#Mann=3,-1,0
  3911.3    0.07       0  4995.4    0.07       0  4999.9    0.07       0
Bank Sta=4995.4,4999.9
Exp/Cntr=0.3,0.1

Type RM Length L Ch R = 1,1326,497,497,497
BEGIN DESCRIPTION:
Bitter Creek Trib6T1 2.0
END DESCRIPTION:
XS GIS Cut Line= 3
      1433955.00      6794388.00      1433549.13      6794890.46
      1433154.99      6795588.01
#Sta/Elev= 30
  4354.1 2511.84  4375.7 2510.99  4382.1 2510.16  4418.4 2509.96  4460.4 2510.54
  4524.4 2508.90  4553.2 2508.68  4624.0 2506.05  4809.0 2501.39  4823.4 2501.38
  4844.2 2500.53  4852.2 2500.68  4894.0 2499.56  4901.8 2498.90  4930.6 2498.64
  4994.5 2496.70  4997.1 2496.10  4997.4 2495.60  5001.3 2495.60  5001.6 2496.10
  5081.4 2498.57  5383.2 2505.30  5426.5 2505.80  5464.1 2507.13  5544.9 2508.91
  5604.1 2509.93  5617.4 2509.73  5653.2 2510.65  5669.1 2510.30  5801.2 2511.84
#Mann=3,-1,0
  4354.1    0.07       0  4997.1    0.07       0  5001.6    0.07       0
Bank Sta=4997.1,5001.6
Exp/Cntr=0.3,0.1

Type RM Length L Ch R = 1,829,499,499,499
BEGIN DESCRIPTION:
Bitter Creek Trib6T1 1.0
END DESCRIPTION:
XS GIS Cut Line= 3
      1433804.98      6794438.01      1433120.03      6794687.86
      1433205.00      6795388.02
#Sta/Elev= 30
  4270.9 2510.40  4286.2 2510.15  4292.2 2509.04  4311.4 2508.14  4397.7 2505.53
  4520.0 2503.36  4545.2 2502.42  4662.1 2499.59  4667.4 2499.81  4739.2 2497.80
  4784.3 2497.33  4824.4 2496.25  4834.8 2496.47  4888.3 2494.93  4926.5 2494.39
  4949.4 2492.87  4949.8 2492.37  4953.7 2492.37  4954.0 2492.87  4973.4 2493.77
  5020.3 2493.79  5030.4 2494.31  5060.6 2494.42  5166.1 2496.51  5322.5 2500.22
  5342.6 2501.04  5416.5 2502.50  5463.5 2504.21  5614.6 2506.90  5705.3 2509.47
#Mann=3,-1,0
  4270.9    0.07       0  4949.4    0.07       0  4954.0    0.07       0
Bank Sta=4949.4,4954
Exp/Cntr=0.3,0.1

Type RM Length L Ch R = 1,330,231,231,231
BEGIN DESCRIPTION:
Bitter Creek Trib6T1 0.1
END DESCRIPTION:
XS GIS Cut Line= 3
      1433554.99      6794288.00      1432835.02      6794367.96
      1432755.00      6795488.00
#Sta/Elev= 30
  4275.6 2505.44  4567.4 2499.70  4864.3 2492.89  4919.5 2492.22  4960.0 2490.73
  4979.9 2490.87  4995.2 2489.69  4995.5 2489.19  4999.4 2489.19  4999.8 2489.69
  5060.2 2491.15  5090.3 2490.68  5270.7 2492.10  5330.9 2493.29  5340.9 2494.37
  5348.5 2493.66  5501.3 2497.23  5581.5 2498.04  5591.5 2498.92  5621.6 2499.08
  5629.2 2499.70  5634.2 2499.28  5671.8 2499.77  5721.9 2501.07  5802.1 2502.09
  5812.1 2502.75  5932.4 2504.27  5992.6 2505.64  6012.6 2505.50  6122.9 2507.84
#Mann=3,-1,0
  4275.6    0.07       0  4995.2    0.07       0  4999.8    0.07       0
Bank Sta=4995.2,4999.8
Exp/Cntr=0.3,0.1

Type RM Length L Ch R = 1,99,0,0,0
BEGIN DESCRIPTION:
Bitter Creek Trib6T1 4184
END DESCRIPTION:
XS GIS Cut Line= 3
      1433074.77      6794141.99      1432634.87      6794288.32
      1432512.23      6794897.19
#Sta/Elev= 30
  4536.4 2495.98  4609.9 2494.71  4652.1 2493.55  4667.1 2493.64  4693.5 2492.50
  4698.8 2492.88  4704.8 2492.25  4725.1 2492.44  4810.2 2490.64  4905.0 2488.24
  4936.6 2486.76  4957.7 2487.13  4997.3 2486.13  5019.8 2486.36  5022.6 2486.02
  5022.9 2485.52  5026.9 2485.52  5027.2 2486.02  5126.6 2487.19  5172.3 2488.65
  5315.9 2491.00  5375.6 2491.60  5387.3 2491.27  5417.9 2492.28  5431.5 2492.18
  5477.2 2493.15  5489.3 2492.77  5528.1 2493.75  5533.2 2493.54  5621.1 2494.92
#Mann=3,-1,0
  4536.4    0.07       0  5022.6    0.07       0  5027.2    0.07       0
Bank Sta=5022.6,5027.2
Exp/Cntr=0.3,0.1

Chan Stop Cuts=-1