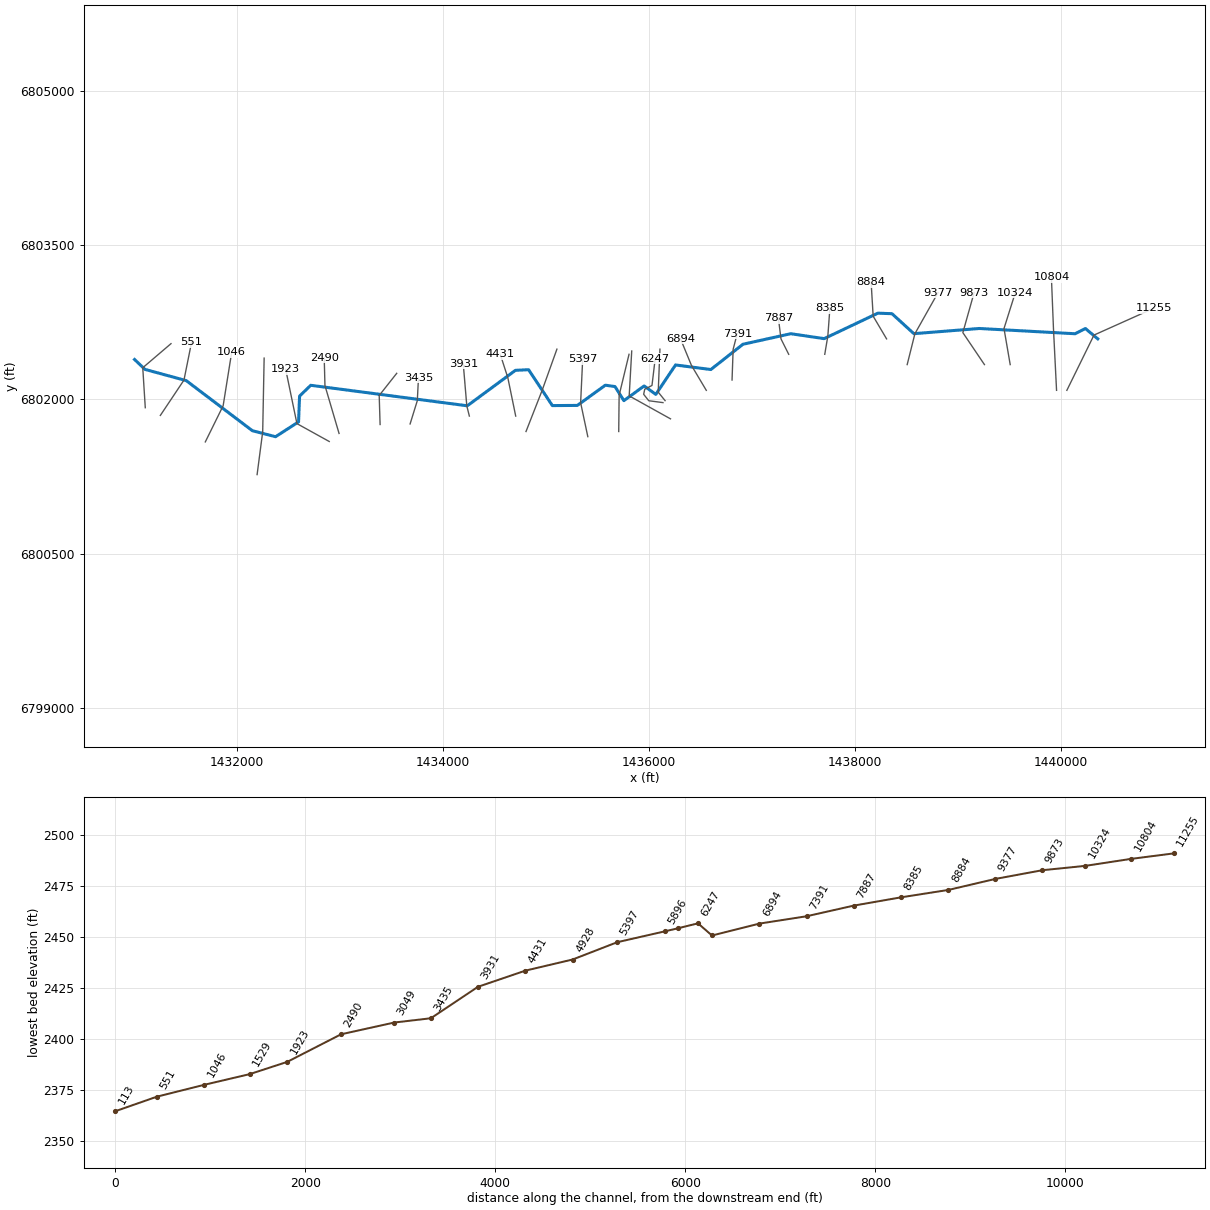
--- Bitter Creek Trib6T2.prj (project) ---

Proj Title=Bitter Creek Trib6T2 Base Level Engineering
Current Plan=p01
Default Exp/Contr=0.3,0.1
English Units
Geom File=g01
Flow File=f01
Plan File=p01
Y Axis Title=Elevation
X Axis Title(PF)=Main Channel Distance
X Axis Title(XS)=Station
BEGIN DESCRIPTION:
Bitter Creek Trib6T2
END DESCRIPTION:
DSS Export Rating Curves= 0
DSS Export Rating Curve Sorted= 0
DSS Export Volume Flow Curves= 0
DXF OffsetX= 0
DXF OffsetY= 0
DXF ScaleX= 1
DXF ScaleY= 10

--- Bitter Creek Trib6T2.p01 (plan) ---

Plan Title=Multiple Run
Short Identifier=Multiple
Geom File=g01
Flow File=f01
Subcritical Flow
K Sum by GR= 0
Std Step Tol= 0.01
Critical Tol= 0.01
Num of Std Step Trials= 20
Max Error Tol= 0.3
Flow Tol Ratio= 0.001
Split Flow NTrial= 30
Split Flow Tol= 0.02
Split Flow Ratio= 0.02
Log Output Level= 0
Friction Slope Method= 1
Unsteady Friction Slope Method= 2
Unsteady Bridges Friction Slope Method= 1
Parabolic Critical Depth
Global Vel Dist=  1 , 1 , 1
Global Log Level= 0
CheckData=True
Encroach Param= -1, 0, 0, 0
BEGIN DESCRIPTION:
Multiple Run
END DESCRIPTION:

--- Bitter Creek Trib6T2.f01 (steady flow) ---

Flow Title=Multiple
Number of Profiles=7
Profile Names=10-year,25-year,50-year,1pct_min,100-year,1pct_plu,500-year
River Rch & RM= Bitter Creek Tri,Reach-1,11255
     290     400     491     299     596    1189     890
River Rch & RM= Bitter Creek Tri,Reach-1,5896
     481     689     866     540    1078    2150    1690
River Rch & RM= Bitter Creek Tri,Reach-1,1529
     721    1064    1365     868    1732    3456    2827
River Rch & RM= Bitter Creek Tri,Reach-1,1046
     644     939    1193     752    1500    2994    2404
Boundary for River Rch & Prof#=Bitter Creek Tri,Reach-1,1
Up Type=0
Dn Type=3
Dn Slope=0.005
Boundary for River Rch & Prof#=Bitter Creek Tri,Reach-1,2
Up Type=0
Dn Type=3
Dn Slope=0.005
Boundary for River Rch & Prof#=Bitter Creek Tri,Reach-1,3
Up Type=0
Dn Type=3
Dn Slope=0.005
Boundary for River Rch & Prof#=Bitter Creek Tri,Reach-1,4
Up Type=0
Dn Type=3
Dn Slope=0.005
Boundary for River Rch & Prof#=Bitter Creek Tri,Reach-1,5
Up Type=0
Dn Type=3
Dn Slope=0.005
Boundary for River Rch & Prof#=Bitter Creek Tri,Reach-1,6
Up Type=0
Dn Type=3
Dn Slope=0.005
Boundary for River Rch & Prof#=Bitter Creek Tri,Reach-1,7
Up Type=0
Dn Type=3
Dn Slope=0.005

--- Bitter Creek Trib6T2.g01 (geometry) ---

Geom Title=Existing Conditions
Program Version=4.10

River Reach=Bitter Creek Tri,Reach-1
Reach XY= 30
        1440355.        6802588.      1440234.86      6802688.42
      1440134.83      6802637.73        1439205.      6802688.81
      1438570.16      6802638.38      1438357.45      6802832.55
      1438220.22      6802837.51      1437699.07      6802590.24
       1437375.1      6802638.09      1436910.97      6802535.67
      1436599.14      6802290.05      1436256.46      6802334.48
       1436065.3      6802048.88      1435951.67      6802130.38
        1435755.        6801988.      1435668.66      6802124.83
       1435575.1      6802138.12      1435303.54      6801941.54
      1435060.67      6801939.98      1434830.12      6802288.32
      1434702.56      6802282.53      1434235.02      6801937.96
      1432715.43      6802136.97      1432607.05      6802032.16
       1432597.2      6801781.79      1432373.92      6801637.58
      1432148.83      6801695.86      1431507.29      6802182.15
      1431106.44      6802291.48        1431005.        6802388.

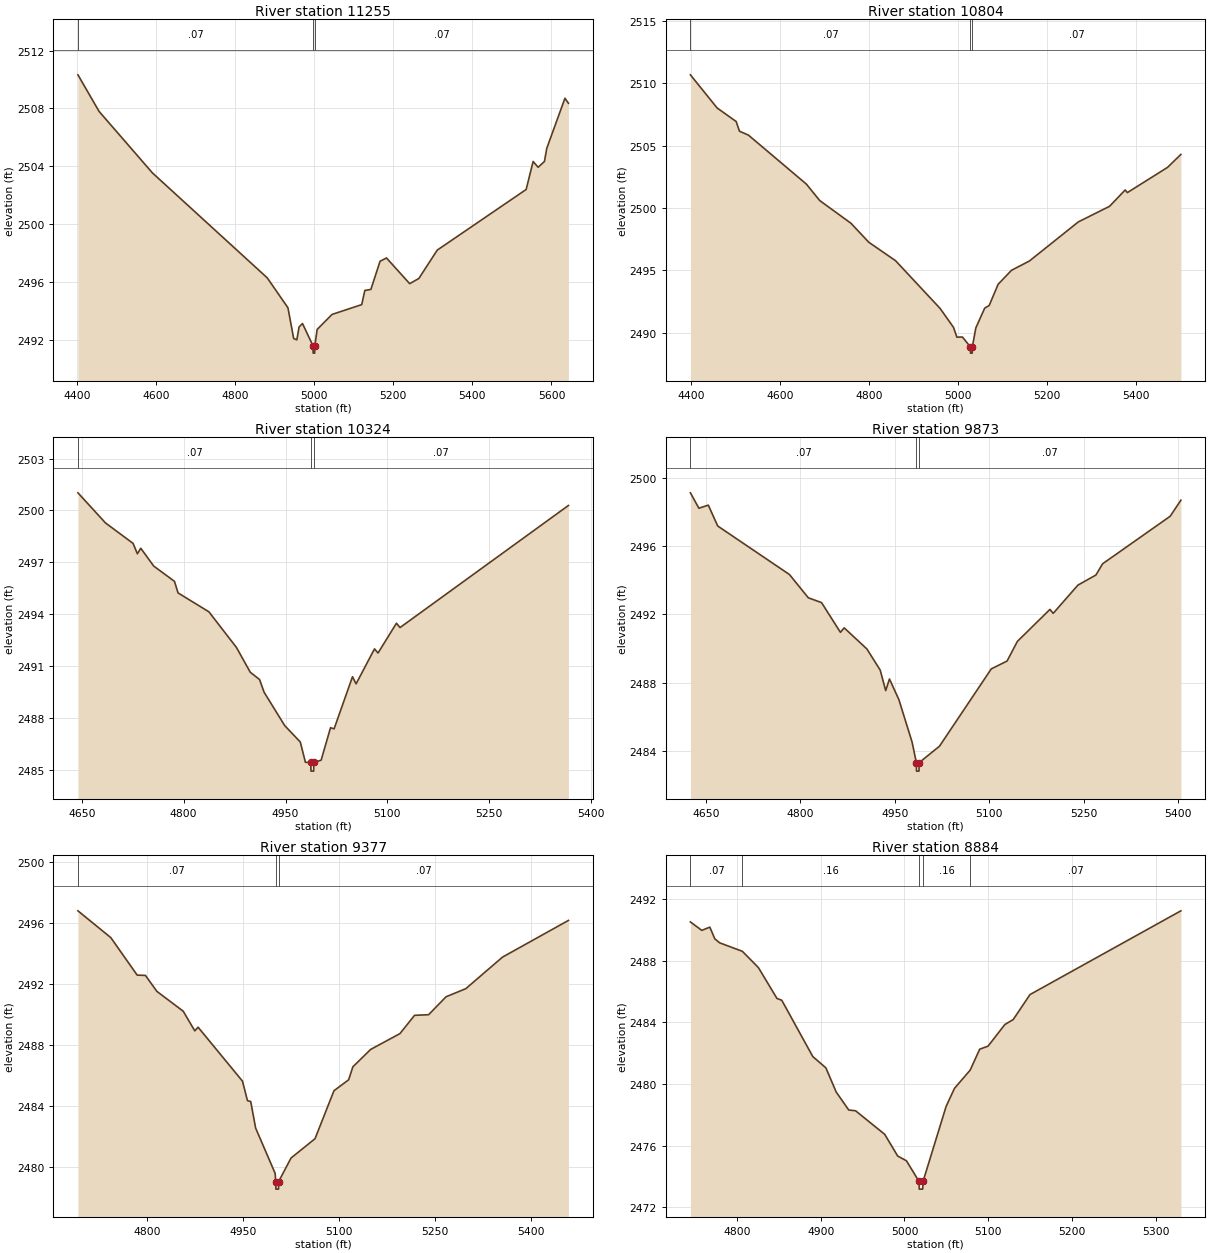
Type RM Length L Ch R = 1 ,11255   ,451,451,451
BEGIN DESCRIPTION:
Bitter Creek Trib6T2 23.0
END DESCRIPTION:
XS GIS Cut Line= 3
        1440055.        6802088.       1440318.4      6802624.87
      1440904.99      6802887.99
#Sta/Elev= 30
    4402 2510.33  4455.4  2507.8  4590.4 2503.54    4881 2496.27  4933.3  2494.2
  4947.8 2492.07  4955.8 2491.98  4961.4 2492.87  4970.1 2493.11  4996.8 2491.56
  4997.1 2491.06  5000.9 2491.06  5001.2 2491.56  5007.2  2492.7  5044.9 2493.74
    5120 2494.42  5127.8  2495.4  5143.1 2495.47  5166.3 2497.42  5182.6 2497.65
  5241.3 2495.87  5264.5 2496.23  5310.9 2498.19  5535.9 2502.39  5553.6 2504.33
  5566.2 2503.93  5582.2 2504.33  5588.1 2505.24  5634.1 2508.71  5642.9 2508.36
#Mann= 3 ,-1 , 0
    4402     .07       0  4996.8     .07       0  5001.2     .07       0
Bank Sta=4996.8,5001.2
XS Rating Curve= 0 ,0
Exp/Cntr=0.3,0.1

Type RM Length L Ch R = 1 ,10804   ,480,480,480
BEGIN DESCRIPTION:
Bitter Creek Trib6T2 22.0
END DESCRIPTION:
XS GIS Cut Line= 3
        1439955.      6802087.97      1439925.01      6802688.02
        1439905.      6803188.02
#Sta/Elev= 30
  4399.2 2510.67  4459.3 2508.01  4501.9 2506.93  4509.4 2506.15  4529.4 2505.84
  4659.6 2501.91  4689.6 2500.59  4759.7 2498.77  4799.7 2497.25  4859.8 2495.77
  4959.9 2491.94    4990 2490.42  4997.5 2489.64    5010 2489.65  5027.8 2488.86
  5028.1 2488.36  5031.9 2488.36  5032.2 2488.86    5040 2490.38    5060 2491.97
    5070 2492.18  5090.1 2493.88  5120.1    2495  5160.1 2495.74  5270.2 2498.88
  5340.3 2500.13  5375.3 2501.44  5380.3 2501.23  5470.4 2503.25  5500.4 2504.29
#Mann= 3 ,-1 , 0
  4399.2     .07       0  5027.8     .07       0  5032.2     .07       0
Bank Sta=5027.8,5032.2
XS Rating Curve= 0 ,0
Exp/Cntr=0.3,0.1

Type RM Length L Ch R = 1 ,10324   ,451,451,451
BEGIN DESCRIPTION:
Bitter Creek Trib6T2 21.0
END DESCRIPTION:
XS GIS Cut Line= 3
        1439505.      6802337.98      1439444.81      6802688.45
        1439555.      6803037.99
#Sta/Elev= 30
  4644.4 2501.02    4685 2499.28  4725.6  2498.1  4731.9  2497.5  4736.9 2497.82
    4756 2496.79  4786.5 2495.91  4791.8 2495.24  4837.2 2494.15  4877.8 2492.09
  4898.1 2490.66  4911.8 2490.24  4918.4 2489.51  4948.8 2487.58  4971.8 2486.63
  4979.3 2485.46  4987.2 2485.45  4987.5 2484.95  4991.4 2484.95  4991.7 2485.45
  5002.4 2485.58  5016.3 2487.46  5021.5 2487.39  5048.6  2490.4  5053.9 2489.99
    5081 2492.01  5086.2 2491.77  5113.3 2493.49  5118.6 2493.24  5366.5 2500.29
#Mann= 3 ,-1 , 0
  4644.4     .07       0  4987.2     .07       0  4991.7     .07       0
Bank Sta=4987.2,4991.7
XS Rating Curve= 0 ,0
Exp/Cntr=0.3,0.1

Type RM Length L Ch R = 1 ,9873    ,496,496,496
BEGIN DESCRIPTION:
Bitter Creek Trib6T2 20.0
END DESCRIPTION:
XS GIS Cut Line= 3
      1439254.98      6802338.03      1439045.47      6802648.57
      1439154.99      6803037.96
#Sta/Elev= 30
  4625.4 2499.11  4638.9 2498.21  4653.9 2498.39  4668.8 2497.17  4782.8 2494.33
  4812.7 2492.97  4833.7 2492.69  4863.7 2490.95  4869.7 2491.21  4905.7 2489.98
  4926.9 2488.74  4935.6 2487.54  4941.6 2488.22  4956.6 2487.01  4977.6 2484.52
  4984.3 2483.33  4984.6 2482.83  4988.5 2482.83  4988.9 2483.33  5021.1 2484.29
  5103.3 2488.81  5128.4 2489.27  5144.8 2490.42  5196.5 2492.29  5201.7 2492.06
  5240.9 2493.71  5269.5  2494.3  5280.2 2494.96  5387.5 2497.74  5404.5 2498.68
#Mann= 3 ,-1 , 0
  4625.4     .07       0  4984.3     .07       0  4988.9     .07       0
Bank Sta=4984.3,4988.9
XS Rating Curve= 0 ,0
Exp/Cntr=0.3,0.1

Type RM Length L Ch R = 1 ,9377    ,493,493,493
BEGIN DESCRIPTION:
Bitter Creek Trib6T2 19.0
END DESCRIPTION:
XS GIS Cut Line= 3
        1438505.      6802338.01      1438579.88       6802637.7
      1438805.02      6803038.04
#Sta/Elev= 30
  4691.1 2496.82  4742.6 2495.06  4783.9  2492.6  4796.8 2492.58  4814.8 2491.53
    4856 2490.23  4874.1 2488.94  4879.3 2489.18  4948.8 2485.64  4956.6 2484.36
  4961.7  2484.3  4969.4 2482.56    5000 2479.58  5000.8 2479.05  5001.2 2478.55
  5005.2 2478.55  5005.5 2479.05  5024.8 2480.59  5062.4 2481.86  5092.1 2485.01
  5115.1 2485.73  5121.7 2486.58  5149.5 2487.72  5195.4 2488.76  5218.3 2489.96
  5240.3    2490  5267.7 2491.18  5298.6 2491.71    5356 2493.78  5459.3 2496.19
#Mann= 3 ,-1 , 0
  4691.1     .07       0  5000.8     .07       0  5005.5     .07       0
Bank Sta=5000.8,5005.5
XS Rating Curve= 0 ,0
Exp/Cntr=0.3,0.1

Type RM Length L Ch R = 1 ,8884    ,499,499,499
BEGIN DESCRIPTION:
Bitter Creek Trib6T2 18.0
END DESCRIPTION:
XS GIS Cut Line= 3
      1438304.98      6802588.03      1438174.89      6802808.28
        1438155.      6803137.98
#Sta/Elev= 30
  4744.2 2490.53  4757.8 2489.98  4767.4 2490.19  4773.4 2489.43  4779.2 2489.17
  4806.3 2488.62  4825.5 2487.56  4847.6 2485.56  4853.4 2485.44  4890.5 2481.78
  4906.1 2481.05  4918.4 2479.48  4933.4 2478.31  4941.6 2478.26  4976.4 2476.73
  4991.9 2475.32  5002.4 2475.01  5017.4 2473.67  5017.7 2473.17  5021.8 2473.17
  5022.2 2473.67  5049.8 2478.55  5059.8 2479.72  5078.5  2480.9  5089.9 2482.26
  5099.9 2482.46  5119.9 2483.86    5130 2484.19    5150 2485.81  5330.3 2491.25
#Mann= 5 ,-1 , 0
  4744.2     .07       0  4806.3     .16       0  5017.4     .07       0
  5022.2     .16       0  5078.5     .07       0
Bank Sta=5017.4,5022.2
XS Rating Curve= 0 ,0
Exp/Cntr=0.3,0.1

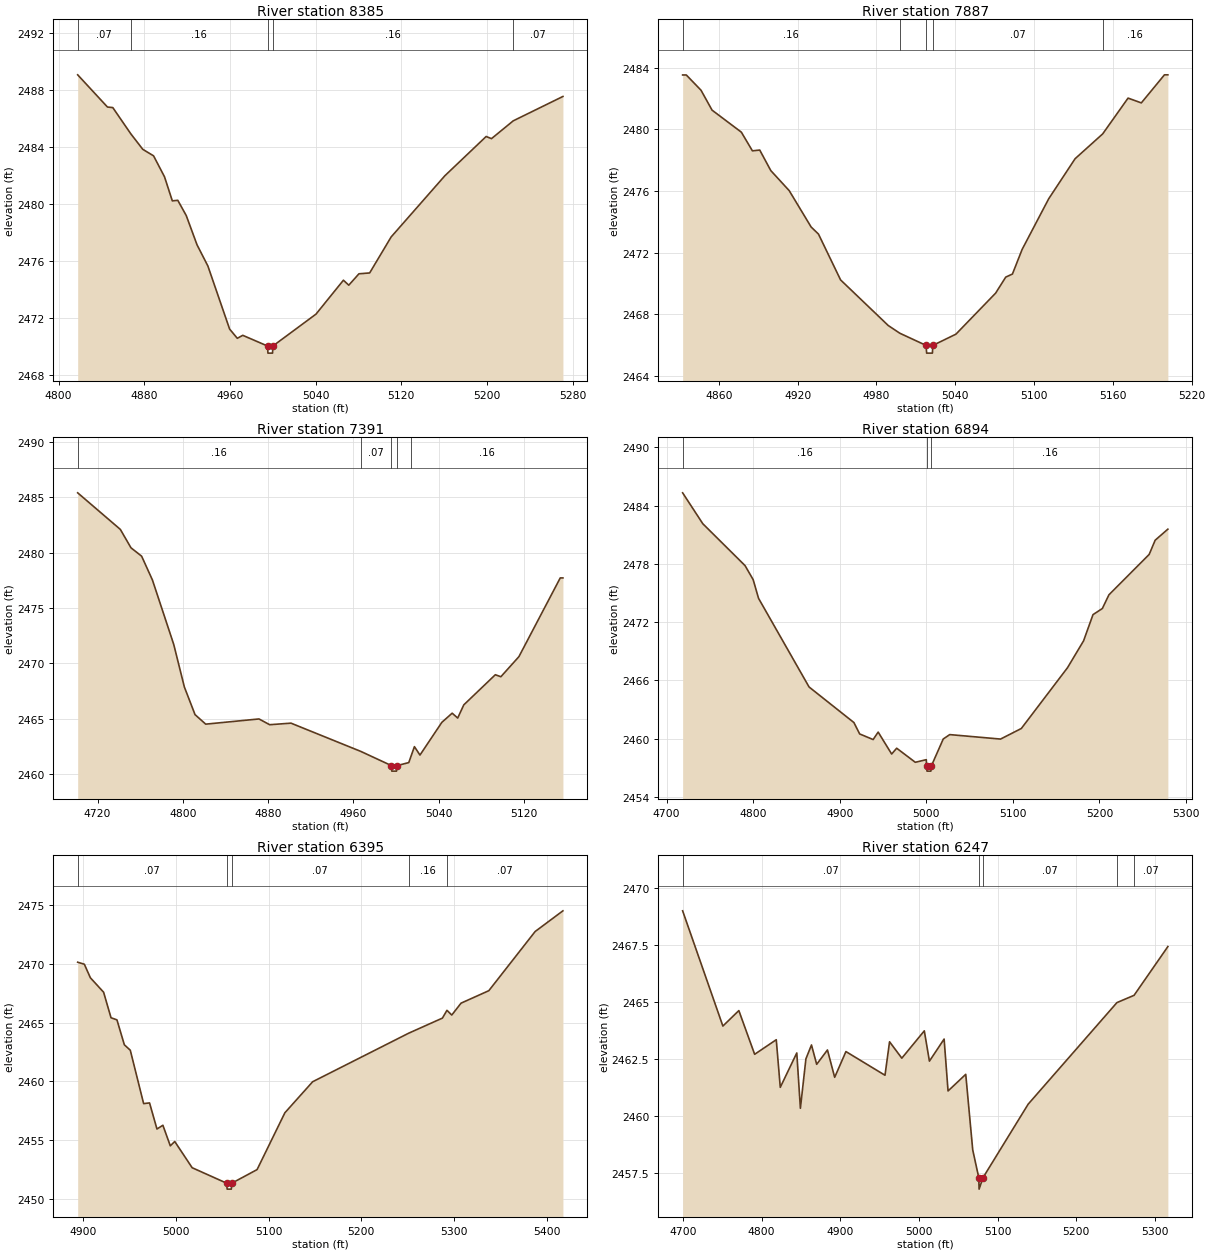
Type RM Length L Ch R = 1 ,8385    ,498,498,498
BEGIN DESCRIPTION:
Bitter Creek Trib6T2 17.0
END DESCRIPTION:
XS GIS Cut Line= 3
        1437705.      6802438.03      1437735.11      6802617.72
        1437755.      6802887.99
#Sta/Elev= 30
  4817.8 2489.08  4845.6 2486.82  4850.6 2486.78  4867.5 2484.93  4878.6 2483.85
  4888.7 2483.39  4898.9 2481.92  4906.2 2480.23  4911.3 2480.27  4919.2  2479.2
  4929.3 2477.14  4939.4 2475.66  4959.7 2471.23  4966.9 2470.58    4972 2470.79
  4995.1 2470.04  4995.5 2469.54  4999.8 2469.54  5000.1 2470.04  5040.4 2472.28
    5066 2474.66    5071 2474.31  5080.5 2475.11  5090.5 2475.17  5110.6  2477.7
  5160.7 2481.99  5199.3 2484.75  5204.3  2484.6  5224.6 2485.85    5271 2487.56
#Mann= 5 ,-1 , 0
  4817.8     .07       0  4867.5     .16       0  4995.1     .07       0
  5000.1     .16       0  5224.6     .07       0
Bank Sta=4995.1,5000.1
XS Rating Curve= 0 ,0
Exp/Cntr=0.3,0.1

Type RM Length L Ch R = 1 ,7887    ,496,496,496
BEGIN DESCRIPTION:
Bitter Creek Trib6T2 16.0
END DESCRIPTION:
XS GIS Cut Line= 3
      1437355.01      6802437.99      1437280.08       6802587.8
        1437255.      6802788.03
#Sta/Elev= 30
  4832.5 2483.52  4835.3 2483.52  4846.5 2482.53  4854.9 2481.24  4877.2 2479.81
  4885.6  2478.6  4891.2 2478.65  4899.6 2477.32  4913.6 2476.02  4930.3 2473.66
  4935.9  2473.2  4952.7 2470.23    4989 2467.27  4997.8 2466.77  5017.8 2465.98
  5018.2 2465.48  5022.6 2465.48  5022.9 2465.98  5040.5 2466.71  5070.7 2469.37
  5078.4 2470.41  5083.5 2470.61  5090.9 2472.21  5111.1 2475.49  5131.2 2478.09
  5152.2  2479.7  5171.5 2482.02  5181.6 2481.71  5199.2 2483.53  5201.8 2483.53
#Mann= 5 ,-1 , 0
  4832.5     .16       0  4997.8     .07       0  5017.8     .07       0
  5022.9     .07       0  5152.2     .16       0
Bank Sta=5017.8,5022.9
XS Rating Curve= 0 ,0
Exp/Cntr=0.3,0.1

Type RM Length L Ch R = 1 ,7391    ,497,497,497
BEGIN DESCRIPTION:
Bitter Creek Trib6T2 15.0
END DESCRIPTION:
XS GIS Cut Line= 3
        1436805.      6802187.99      1436815.62       6802486.5
      1436854.99      6802637.97
#Sta/Elev= 30
  4701.3 2485.39  4741.3 2482.09  4751.3 2480.43  4761.3 2479.67  4771.4 2477.53
  4791.4 2471.71  4801.4 2467.86  4811.4 2465.37  4821.4 2464.51  4871.4 2464.98
  4881.4 2464.46  4901.4  2464.6  4966.9 2462.05  4995.6 2460.77    4996 2460.27
  5000.4 2460.27  5000.9 2460.77  5011.9 2461.04  5014.1 2461.64  5017.2 2462.48
  5022.4 2461.72  5042.9 2464.67  5052.6  2465.5  5057.8 2465.06  5063.5 2466.25
  5093.1 2468.97  5098.3 2468.79  5115.2  2470.6    5154 2477.71  5156.5 2477.71
#Mann= 5 ,-1 , 0
  4701.3     .16       0  4966.9     .07       0  4995.6     .07       0
  5000.9     .07       0  5014.1     .16       0
Bank Sta=4995.6,5000.9
XS Rating Curve= 0 ,0
Exp/Cntr=0.3,0.1

Type RM Length L Ch R = 1 ,6894    ,499,499,499
BEGIN DESCRIPTION:
Bitter Creek Trib6T2 14.0
END DESCRIPTION:
XS GIS Cut Line= 3
      1436555.02      6802087.96      1436411.05      6802329.86
      1436304.99      6802588.02
#Sta/Elev= 30
  4718.5 2485.32  4741.8 2482.14  4790.6 2477.83    4800 2476.38  4806.2 2474.46
  4864.6 2465.33  4916.4 2461.67    4923  2460.5  4938.6 2459.92  4944.4 2460.69
    4960 2458.43  4965.8 2459.03  4987.3 2457.58    5000 2457.85  5000.4 2457.17
  5000.8 2456.67  5005.3 2456.67  5005.7 2457.17  5019.6 2459.98  5027.1 2460.43
  5085.8 2459.97  5109.8 2461.06  5163.1 2467.31  5181.7 2470.08  5192.6 2472.78
  5203.4 2473.41    5211 2474.82  5257.5 2478.98  5264.4 2480.44  5279.1 2481.58
#Mann= 3 ,-1 , 0
  4718.5     .16       0  5000.4     .07       0  5005.7     .16       0
Bank Sta=5000.4,5005.7
XS Rating Curve= 0 ,0
Exp/Cntr=0.3,0.1

Type RM Length L Ch R = 1 ,6395    ,148,148,148
BEGIN DESCRIPTION:
Bitter Creek Trib6T2 13.0
END DESCRIPTION:
XS GIS Cut Line= 3
      1436155.03      6801987.97       1436088.3      6802070.58
        1436105.      6802487.95
#Sta/Elev= 30
  4893.8 2470.13    4901 2469.96  4907.5 2468.81  4921.8 2467.58  4929.8 2465.41
  4936.2 2465.23  4944.2 2463.11  4950.6 2462.65    4965 2458.11  4971.4 2458.17
  4979.4 2455.95  4985.8 2456.27  4993.8 2454.52  4998.6 2454.89  5017.4 2452.66
  5054.8 2451.34  5055.2 2450.84  5059.7 2450.84  5060.1 2451.34  5087.5  2452.5
  5117.5 2457.33  5147.5 2459.97    5251 2464.09  5287.6 2465.38  5292.5 2466.04
  5297.7 2465.64  5307.7 2466.65  5337.7 2467.71  5387.7 2472.74  5417.7  2474.5
#Mann= 5 ,-1 , 0
  4893.8     .07       0  5054.8     .07       0  5060.1     .07       0
    5251     .16       0  5292.5     .07       0
Bank Sta=5054.8,5060.1
XS Rating Curve= 0 ,0
Exp/Cntr=0.3,0.1

Type RM Length L Ch R = 1 ,6247    ,212,212,212
BEGIN DESCRIPTION:
Bitter Creek Trib6T2 4298
END DESCRIPTION:
XS GIS Cut Line= 6
      1436134.61      6801968.73      1435996.57      6801986.96
      1435947.09      6802049.46      1435957.51      6802098.94
      1436027.82       6802135.4       1436058.9      6802394.44
#Sta/Elev= 30
  4699.5 2469.01  4750.7 2463.95    4771 2464.63  4791.1 2462.71  4818.6 2463.35
  4823.7 2461.26  4844.7 2462.77  4849.3 2460.34  4856.3 2462.51  4863.4 2463.12
    4870 2462.27  4883.7  2462.9  4892.9  2461.7  4907.2 2462.83  4956.9 2461.79
  4962.7 2463.26  4978.3 2462.54  5006.9 2463.74  5013.4 2462.41  5032.1 2463.38
  5037.1  2461.1  5059.6 2461.83  5068.5 2458.51  5076.2 2457.29  5076.6 2456.79
  5081.5 2457.29    5139 2460.52  5251.9 2464.98  5273.7  2465.3  5316.7 2467.44
#Mann= 5 ,-1 , 0
  4699.5     .07       0  5076.2     .07       0  5081.5     .07       0
  5251.9     .16       0  5273.7     .07       0
Bank Sta=5076.2,5081.5
XS Rating Curve= 0 ,0
Exp/Cntr=0.3,0.1

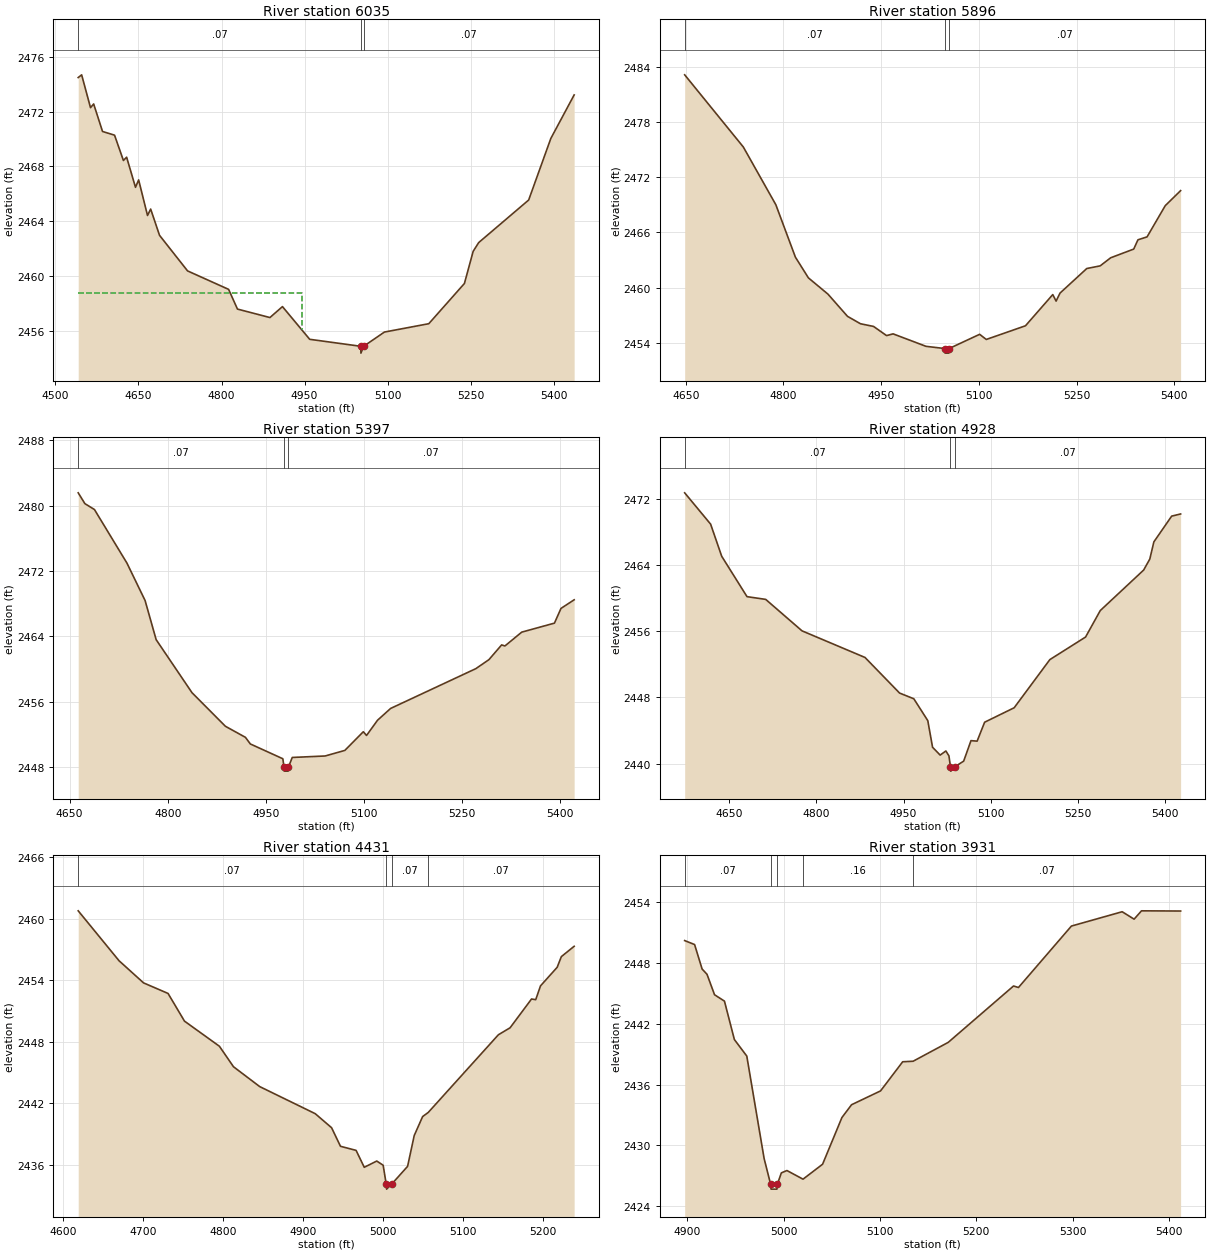
Type RM Length L Ch R = 1 ,6035    ,139,139,139
BEGIN DESCRIPTION:
Bitter Creek Trib6T2 4299
END DESCRIPTION:
XS GIS Cut Line= 3
      1436207.51      6801811.18      1435806.62      6802034.09
       1435831.2        6802470.
#Sta/Elev= 30
  4541.3  2474.5  4547.5  2474.7  4563.5  2472.3  4569.2 2472.57  4585.2 2470.56
  4606.9 2470.29  4622.9 2468.44  4628.7 2468.68  4644.7 2466.48  4650.4 2467.02
  4666.4 2464.42  4672.1 2464.89  4688.1 2462.97  4738.7 2460.37  4812.8 2459.02
  4828.8 2457.58  4887.4 2456.96    4910 2457.76  4959.2 2455.37  5051.3 2454.86
  5051.7 2454.36  5056.6 2454.86  5094.1  2455.9  5174.2 2456.51  5238.5 2459.45
  5254.3  2461.8  5264.3 2462.44  5354.5 2465.55  5394.5 2470.05  5436.6 2473.23
#Mann= 3 ,-1 , 0
  4541.3     .07       0  5051.3     .07       0  5056.6     .07       0
#XS Ineff= 2 , 0
         4945.19 2458.77
Permanent Ineff=
       F       F
Bank Sta=5051.3,5056.6
XS Rating Curve= 0 ,0
Exp/Cntr=0.3,0.1

Type RM Length L Ch R = 1 ,5896    ,499,499,499
BEGIN DESCRIPTION:
Bitter Creek Trib6T2 12.0
END DESCRIPTION:
XS GIS Cut Line= 3
        1435705.      6801687.98      1435708.93      6802039.66
      1435805.01      6802438.04
#Sta/Elev= 30
  4648.3 2483.18  4738.3 2475.32  4788.3 2469.02  4818.3 2463.31  4838.3 2461.05
  4868.3 2459.28  4898.3 2456.86  4918.3 2456.05  4938.3 2455.76  4958.3 2454.76
  4968.3 2454.95  5018.9 2453.59  5047.7 2453.35  5048.2 2452.85  5053.8 2452.85
  5054.3 2453.35  5101.2  2454.9  5111.4 2454.34  5171.6 2455.83  5213.5 2459.23
  5218.6 2458.52  5224.6 2459.39  5265.7 2462.07  5286.3 2462.36  5302.4 2463.24
  5337.8 2464.19  5344.3  2465.2  5358.3 2465.52  5386.2 2468.92  5409.8 2470.56
#Mann= 3 ,-1 , 0
  4648.3     .07       0  5047.7     .07       0  5054.3     .07       0
Bank Sta=5047.7,5054.3
XS Rating Curve= 0 ,0
Exp/Cntr=0.3,0.1

Type RM Length L Ch R = 1 ,5397    ,469,469,469
BEGIN DESCRIPTION:
Bitter Creek Trib6T2 11.0
END DESCRIPTION:
XS GIS Cut Line= 3
        1435405.      6801638.02       1435335.2      6801967.51
        1435355.      6802388.04
#Sta/Elev= 30
  4663.2 2481.55  4673.4 2480.23    4688 2479.51  4737.7 2472.96  4765.4 2468.39
  4782.3 2463.61  4837.1 2457.13  4888.1 2453.03  4918.7 2451.68  4926.2 2450.87
  4975.9 2449.06  4977.6 2448.05  4978.1 2447.55  4983.9 2447.55  4984.4 2448.05
  4990.3 2449.22  5040.5  2449.4  5070.6 2450.08  5098.8 2452.36  5103.8 2451.91
  5120.6 2453.77  5140.6 2455.21  5270.8 2460.07  5290.8 2461.17  5310.2 2462.97
  5315.2 2462.84  5340.9 2464.53  5390.9 2465.63  5400.9 2467.43    5421 2468.48
#Mann= 3 ,-1 , 0
  4663.2     .07       0  4977.6     .07       0  4984.4     .07       0
Bank Sta=4977.6,4984.4
XS Rating Curve= 0 ,0
Exp/Cntr=0.3,0.1

Type RM Length L Ch R = 1 ,4928    ,497,497,497
BEGIN DESCRIPTION:
Bitter Creek Trib6T2 10.0
END DESCRIPTION:
XS GIS Cut Line= 3
        1434805.        6801688.      1434960.77      6802085.68
        1435105.        6802488.
#Sta/Elev= 30
  4572.9 2472.77  4617.6 2468.98  4636.7 2465.09  4680.3  2460.2  4712.5 2459.87
  4775.1 2456.06  4883.6 2452.84  4943.2 2448.53  4967.7 2447.84  4991.8 2445.19
    5000 2441.97  5013.1 2441.02  5022.9 2441.52  5028.2 2440.93  5030.9 2439.58
  5031.4 2439.08  5037.8 2439.58  5053.6 2440.29  5066.2 2442.77  5076.8 2442.71
  5089.7    2445  5140.6 2446.75  5202.1 2452.58  5263.6 2455.31    5289 2458.52
  5363.7 2463.42  5374.3 2464.75  5381.3 2466.83    5412 2469.95  5427.4 2470.21
#Mann= 3 ,-1 , 0
  4572.9     .07       0  5030.9     .07       0  5037.8     .07       0
Bank Sta=5030.9,5037.8
XS Rating Curve= 0 ,0
Exp/Cntr=0.3,0.1

Type RM Length L Ch R = 1 ,4431    ,500,500,500
BEGIN DESCRIPTION:
Bitter Creek Trib6T2 9.0
END DESCRIPTION:
XS GIS Cut Line= 3
      1434704.99      6801838.04      1434628.44      6802211.07
      1434555.01      6802437.98
#Sta/Elev= 30
  4619.2 2460.78  4670.2 2455.91  4700.8 2453.75  4731.4 2452.72  4751.9 2450.02
  4795.5 2447.57  4813.1 2445.57  4845.9 2443.63  4915.2 2440.99  4935.6 2439.62
  4946.7 2437.81  4966.2 2437.41  4976.4 2435.76    4992 2436.37    5000 2435.96
  5003.8 2434.13  5004.3 2433.63  5010.8 2434.13  5030.5 2435.85  5038.8 2438.86
  5049.3 2440.71  5056.3 2441.11  5143.9 2448.69  5158.5 2449.37  5185.3 2452.18
  5190.5 2452.11  5196.5 2453.46  5217.3 2455.27  5222.5 2456.31  5238.5 2457.32
#Mann= 4 ,-1 , 0
  4619.2     .07       0  5003.8     .07       0  5010.8     .07       0
  5056.3     .07       0
Bank Sta=5003.8,5010.8
XS Rating Curve= 0 ,0
Exp/Cntr=0.3,0.1

Type RM Length L Ch R = 1 ,3931    ,496,496,496
BEGIN DESCRIPTION:
Bitter Creek Trib6T2 8.0
END DESCRIPTION:
XS GIS Cut Line= 4
      1434255.01      6801837.96      1434230.12       6801937.7
        1434205.        6802238.      1434195.76      6802348.47
#Sta/Elev= 30
  4897.2 2450.17  4907.5 2449.78  4915.3 2447.37  4920.4 2446.85  4928.2 2444.84
  4938.5 2444.21  4948.8 2440.43  4961.7  2438.8  4979.7 2428.71  4986.4  2426.2
  4986.9  2425.7    4993  2425.7  4993.5  2426.2  4997.6  2427.3  5003.4 2427.53
  5020.1 2426.68  5040.4 2428.15  5060.5 2432.75  5070.5 2434.01  5100.6 2435.37
  5123.6 2438.24  5134.4 2438.29  5170.9 2440.15  5238.7  2445.7  5243.8 2445.55
  5298.8  2451.6  5351.5 2453.01  5363.9 2452.28  5371.6  2453.1  5412.2 2453.08
#Mann= 5 ,-1 , 0
  4897.2     .07       0  4986.4     .07       0  4993.5     .07       0
  5020.1     .16       0  5134.4     .07       0
Bank Sta=4986.4,4993.5
XS Rating Curve= 0 ,0
Exp/Cntr=0.3,0.1

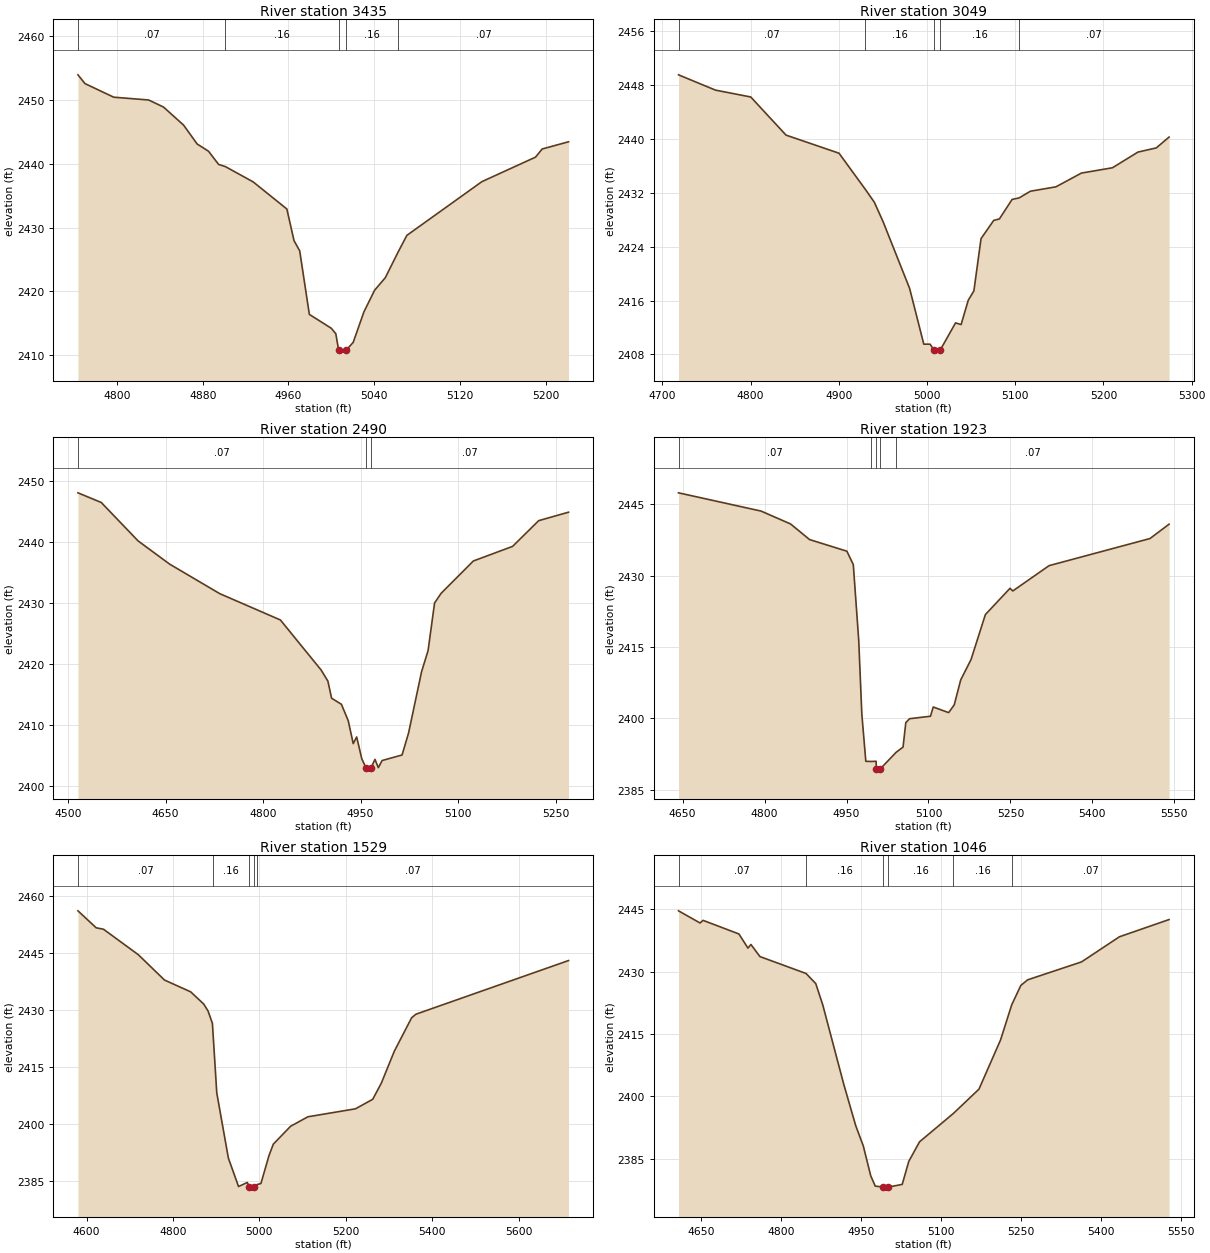
Type RM Length L Ch R = 1 ,3435    ,386,386,386
BEGIN DESCRIPTION:
Bitter Creek Trib6T2 7.0
END DESCRIPTION:
XS GIS Cut Line= 4
      1433679.94      6801761.69      1433749.84      6801987.62
        1433755.        6802088.       1433761.2      6802208.73
#Sta/Elev= 30
  4763.5 2453.97  4770.1 2452.59  4796.9 2450.46  4829.5 2450.02  4843.4 2448.91
  4862.1 2446.08  4874.8 2443.11  4885.3 2441.99  4894.8 2439.91  4901.2 2439.56
  4927.1 2437.16  4958.5 2432.91  4965.2 2427.94  4970.5 2426.34  4979.5 2416.37
    5000 2414.19  5004.2 2413.33  5006.8 2410.79  5007.3 2410.29    5014 2410.79
  5020.4 2411.97  5030.4 2416.75  5040.4 2420.16  5050.4 2422.13  5062.4 2426.17
  5070.5 2428.77  5140.6 2437.21  5190.6 2441.05  5196.8 2442.33  5221.4 2443.46
#Mann= 5 ,-1 , 0
  4763.5     .07       0  4901.2     .16       0  5006.8     .07       0
    5014     .16       0  5062.4     .07       0
Bank Sta=5006.8,5014
XS Rating Curve= 0 ,0
Exp/Cntr=0.3,0.1

Type RM Length L Ch R = 1 ,3049    ,559,559,559
BEGIN DESCRIPTION:
Bitter Creek Trib6T2 6.0
END DESCRIPTION:
XS GIS Cut Line= 3
      1433388.72      6801756.14      1433379.92       6802037.8
       1433549.8      6802253.29
#Sta/Elev= 30
  4718.2 2449.51  4760.1 2447.24  4800.1 2446.22  4840.1 2440.56  4900.2 2437.87
  4930.1 2432.49  4940.2  2430.6  4950.2 2427.69  4980.2 2417.81  4996.3 2409.52
  5003.4 2409.52  5007.8 2408.69  5008.3 2408.19  5015.1 2408.69  5032.3 2412.68
  5038.6 2412.43  5046.7 2416.04  5053.1 2417.43  5061.2 2425.19  5075.6  2427.9
    5082 2428.11  5096.4 2431.01  5104.3 2431.23  5117.2 2432.23  5146.1 2432.88
    5175 2434.92  5210.2 2435.71  5239.1 2438.04  5259.9 2438.66  5274.4 2440.27
#Mann= 5 ,-1 , 0
  4718.2     .07       0  4930.1     .16       0  5007.8     .07       0
  5015.1     .16       0  5104.3     .07       0
Bank Sta=5007.8,5015.1
XS Rating Curve= 0 ,0
Exp/Cntr=0.3,0.1

Type RM Length L Ch R = 1 ,2490    ,567,567,567
BEGIN DESCRIPTION:
Bitter Creek Trib6T2 5.0
END DESCRIPTION:
XS GIS Cut Line= 3
      1432990.27      6801669.24      1432853.43      6802134.23
       1432846.2      6802403.93
#Sta/Elev= 30
  4515.3 2448.12  4551.1 2446.54  4607.8 2440.23  4656.3 2436.42  4733.4 2431.57
  4826.7 2427.25  4889.3 2419.04  4899.7 2417.22  4905.4 2414.41  4920.5 2413.41
    4931 2410.72  4938.7 2406.95    4944 2408.05  4951.8 2404.48  4958.5 2402.94
    4959 2402.44  4965.9 2402.94  4972.1 2404.37  4977.3 2403.01  4983.1 2404.18
  5013.8 2405.09  5023.8  2408.7  5043.8 2418.76  5053.8 2422.22  5063.8 2430.04
  5073.8 2431.62  5123.4 2436.93  5183.8 2439.33  5223.9 2443.55  5269.8 2444.94
#Mann= 3 ,-1 , 0
  4515.3     .07       0  4958.5     .07       0  4965.9     .07       0
Bank Sta=4958.5,4965.9
XS Rating Curve= 0 ,0
Exp/Cntr=0.3,0.1

Type RM Length L Ch R = 1 ,1923    ,394,394,394
BEGIN DESCRIPTION:
Bitter Creek Trib6T2 4.0
END DESCRIPTION:
XS GIS Cut Line= 3
      1432894.86      6801591.15      1432581.28      6801764.89
      1432472.08      6802293.02
#Sta/Elev= 30
  4642.5 2447.43  4793.7 2443.59  4847.5 2440.89  4882.4  2437.6  4950.6 2435.16
  4962.4 2432.34  4972.3 2416.45    4978  2400.9  4985.3 2390.98  4995.3 2390.95
  5004.1 2390.99  5004.6 2389.42  5005.1 2388.92    5012 2389.42  5040.8 2392.88
  5053.4 2393.97  5058.5 2399.13  5065.4 2399.94  5103.6 2400.46  5108.7  2402.4
  5136.9 2401.22  5147.1 2402.85    5159 2408.11  5177.8 2412.36  5204.1 2421.83
  5249.2 2427.36  5254.3  2426.8  5320.7 2432.12  5505.4 2437.82  5540.3 2440.84
#Mann= 5 ,-1 , 0
  4642.5     .07       0  4995.3     .16       0  5004.6     .07       0
    5012     .16       0  5040.8     .07       0
Bank Sta=5004.6,5012
XS Rating Curve= 0 ,0
Exp/Cntr=0.3,0.1

Type RM Length L Ch R = 1 ,1529    ,483,483,483
BEGIN DESCRIPTION:
Bitter Creek Trib6T2 3.0
END DESCRIPTION:
XS GIS Cut Line= 3
      1432194.74       6801269.4      1432249.08      6801685.77
      1432263.05      6802401.03
#Sta/Elev= 30
  4580.1 2456.02  4622.4 2451.56  4639.2 2451.19  4719.9 2444.49  4780.4 2437.84
  4840.9 2434.75  4871.1 2431.55  4881.2 2429.71  4891.3 2426.46  4892.6 2424.11
  4901.4 2408.19  4928.2  2391.1  4951.8 2383.61    4972 2384.68  4977.1 2383.43
  4977.6 2382.93    4987 2383.43  4993.4 2384.08  5003.6 2384.41  5022.2 2391.74
  5032.2 2394.74  5072.2 2399.44  5112.3 2401.93  5222.3 2404.02  5262.3 2406.52
  5282.3 2410.79  5312.3 2419.16  5352.3 2427.93  5362.3 2428.87  5715.4 2442.96
#Mann= 5 ,-1 , 0
  4580.1     .07       0  4892.6     .16       0  4977.1     .07       0
    4987     .16       0  4993.4     .07       0
Bank Sta=4977.1,4987
XS Rating Curve= 0 ,0
Exp/Cntr=0.3,0.1

Type RM Length L Ch R = 1 ,1046    ,495,495,495
BEGIN DESCRIPTION:
Bitter Creek Trib6T2 2.0
END DESCRIPTION:
XS GIS Cut Line= 4
      1431692.01      6801587.07      1431865.14      6801938.43
        1431905.        6802188.      1431948.45      6802460.02
#Sta/Elev= 30
  4608.3 2444.63  4648.7  2441.7  4654.3 2442.34  4721.6 2439.06  4738.5 2435.66
  4744.1 2436.53    4761 2433.62  4847.5 2429.55  4865.7 2427.11  4878.9 2421.95
  4918.2 2402.87  4940.7 2392.89  4954.9 2388.01  4968.7 2380.88  4977.2 2378.38
    4992 2378.15  4992.5 2377.65    5002 2378.15  5027.8 2378.79  5040.1 2384.33
  5060.3 2389.04  5123.6 2395.85  5171.7 2401.71  5212.2 2413.56  5233.1    2422
  5250.2 2426.67  5262.9 2428.02  5364.1 2432.34    5435 2438.38  5528.2 2442.53
#Mann= 6 ,-1 , 0
  4608.3     .07       0  4847.5     .16       0    4992     .07       0
    5002     .16       0  5123.6     .16       0  5233.1     .07       0
Bank Sta=4992,5002
XS Rating Curve= 0 ,0
Exp/Cntr=0.3,0.1

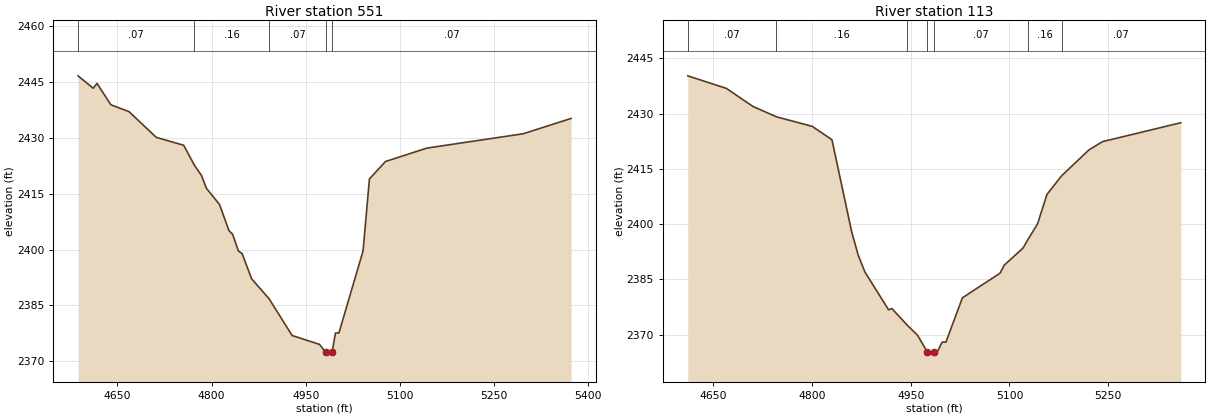
Type RM Length L Ch R = 1 ,551     ,438,438,438
BEGIN DESCRIPTION:
Bitter Creek Trib6T2 1.0
END DESCRIPTION:
XS GIS Cut Line= 4
      1431255.62       6801844.5      1431484.87      6802187.67
        1431505.        6802288.      1431558.14      6802552.79
#Sta/Elev= 30
  4587.3  2446.7  4611.4 2443.36  4617.4 2444.67  4639.6  2438.9  4668.4 2437.08
  4711.8 2430.16  4755.5 2428.03  4772.4  2422.7  4783.9 2419.89  4791.6 2416.48
  4812.6  2412.1  4827.6 2405.09  4833.6 2404.04  4842.6 2399.62  4848.6 2398.88
  4863.7 2392.11  4891.5 2386.76  4928.2 2376.88  4971.8 2374.49  4981.7 2372.37
  4982.2 2371.87  4991.8 2372.37  4997.2 2377.56  5002.7 2377.56  5041.1 2399.59
  5051.3 2418.98  5076.9 2423.67  5143.1 2427.28  5296.1 2431.12  5372.4 2435.24
#Mann= 5 ,-1 , 0
  4587.3     .07       0  4772.4     .16       0  4891.5     .07       0
  4981.7     .07       0  4991.8     .07       0
Bank Sta=4981.7,4991.8
XS Rating Curve= 0 ,0
Exp/Cntr=0.3,0.1

Type RM Length L Ch R = 1 ,113     ,0,0,0
BEGIN DESCRIPTION:
Bitter Creek Trib6T2 4304
END DESCRIPTION:
XS GIS Cut Line= 3
       1431109.3      6801919.27      1431084.79       6802307.5
      1431358.89       6802541.5
#Sta/Elev= 30
    4611 2440.29  4669.8 2436.87  4709.9    2432  4745.5 2429.18  4800.1 2426.58
  4830.2 2422.95  4860.2 2397.92  4870.2 2391.56  4880.3 2387.04  4916.3 2376.77
  4921.3 2377.11    4945 2372.54  4960.4 2369.86  4975.4 2365.24  4975.9 2364.74
  4985.5 2365.24  4990.5  2365.4  4997.7    2368  5003.4    2368  5028.5 2380.03
  5085.6  2386.7  5092.3 2388.94  5120.7 2393.54  5128.6 2395.98  5142.7 2400.09
    5157 2408.09  5179.5 2413.19  5220.7 2420.16  5241.5 2422.43  5360.4 2427.55
#Mann= 7 ,-1 , 0
    4611     .07       0  4745.5     .16       0    4945     .07       0
  4975.4     .07       0  4985.5     .07       0  5128.6     .16       0
  5179.5     .07       0
Bank Sta=4975.4,4985.5
XS Rating Curve= 0 ,0
Exp/Cntr=0.3,0.1

Chan Stop Cuts=-1
Use User Specified Reach Order=0
Composite Channel Slope=5