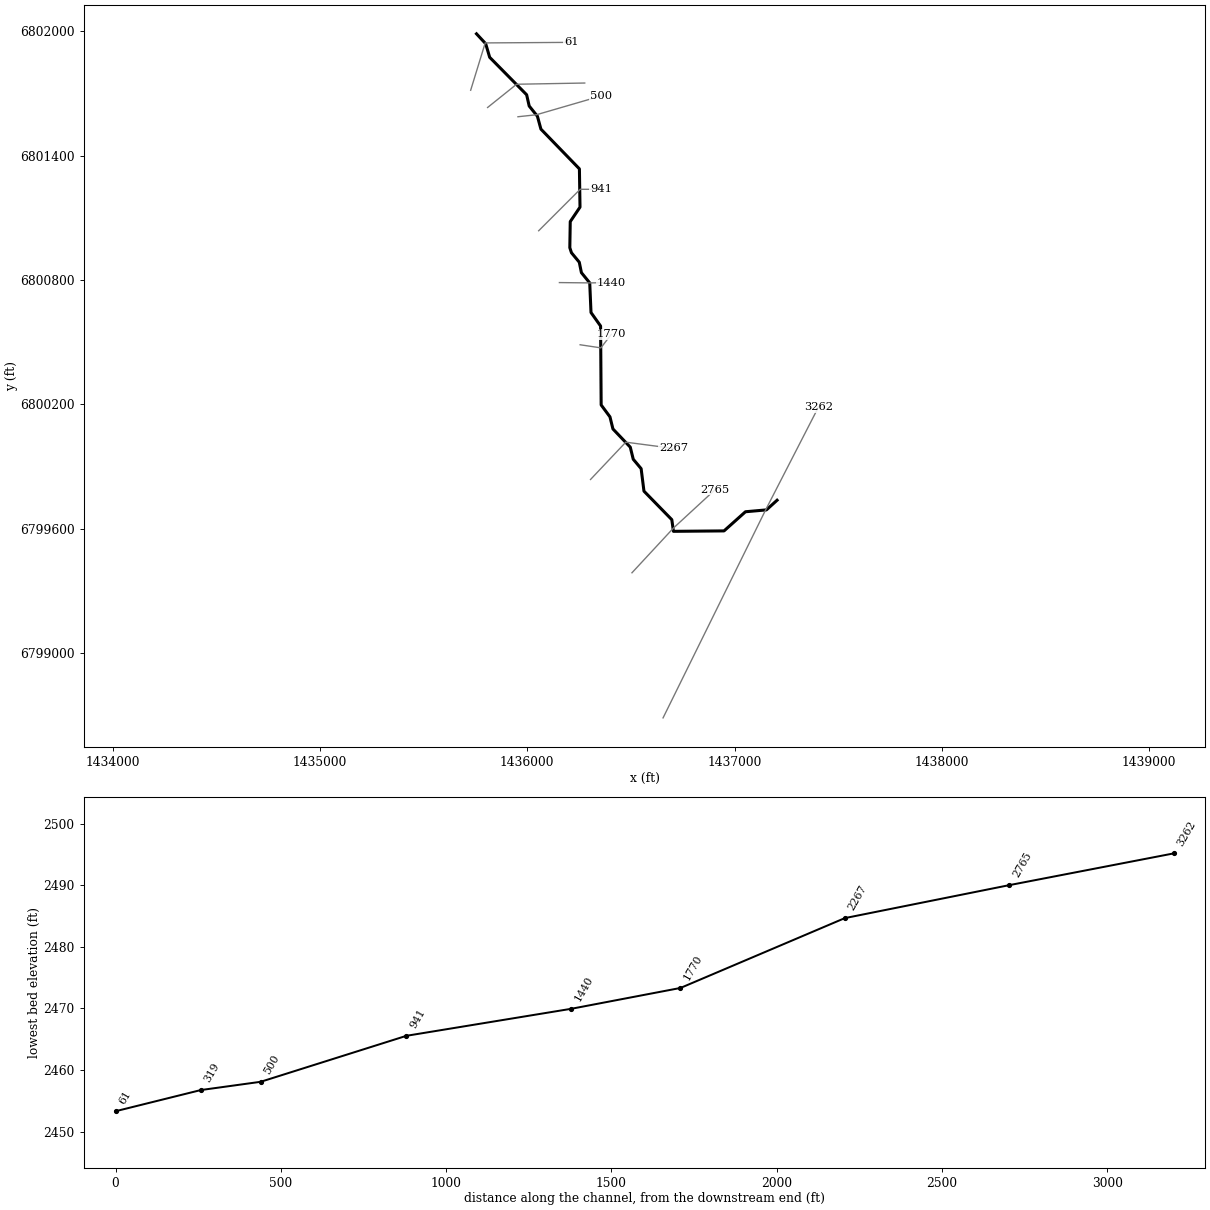
--- Bitter Creek Trib6T2_1.prj (project) ---

Proj Title=Bitter Creek Trib6T2_1 Base Level Engineering
Current Plan=p01
Default Exp/Contr=0.3,0.1
English Units
Geom File=g01
Flow File=f01
Plan File=p01
Y Axis Title=Elevation
X Axis Title(PF)=Main Channel Distance
X Axis Title(XS)=Station
BEGIN DESCRIPTION:
Bitter Creek Trib6T2_1
END DESCRIPTION:
DSS Export Rating Curves= 0
DSS Export Rating Curve Sorted= 0
DSS Export Volume Flow Curves= 0
DXF OffsetX= 0
DXF OffsetY= 0
DXF ScaleX= 1
DXF ScaleY= 10

--- Bitter Creek Trib6T2_1.p01 (plan) ---

Plan Title=Multiple Run
Short Identifier=Multiple
Geom File=g01
Flow File=f01
Subcritical Flow
K Sum by GR= 0
Std Step Tol= 0.01
Critical Tol= 0.01
Num of Std Step Trials= 20
Max Error Tol= 0.3
Flow Tol Ratio= 0.001
Split Flow NTrial= 30
Split Flow Tol= 0.02
Split Flow Ratio= 0.02
Log Output Level= 0
Friction Slope Method= 1
Unsteady Friction Slope Method= 2
Unsteady Bridges Friction Slope Method= 1
Parabolic Critical Depth
Global Vel Dist=  1 , 1 , 1
Global Log Level= 0
CheckData=True
Encroach Param= -1, 0, 0, 0
BEGIN DESCRIPTION:
Multiple Run
END DESCRIPTION:

--- Bitter Creek Trib6T2_1.f01 (steady flow) ---

Flow Title=Multiple
Program Version=4.10
Number of Profiles= 7
Profile Names=10-year,25-year,50-year,1pct_min,100-year,1pct_plu,500-year
River Rch & RM=Bitter Creek Tri,Reach-1         ,3262
     481     689     866     540    1078    2150    1690
Boundary for River Rch & Prof#=Bitter Creek Tri,Reach-1         , 1
Up Type= 0
Dn Type= 3
Dn Slope=0.013
Boundary for River Rch & Prof#=Bitter Creek Tri,Reach-1         , 2
Up Type= 0
Dn Type= 3
Dn Slope=0.013
Boundary for River Rch & Prof#=Bitter Creek Tri,Reach-1         , 3
Up Type= 0
Dn Type= 3
Dn Slope=0.013
Boundary for River Rch & Prof#=Bitter Creek Tri,Reach-1         , 4
Up Type= 0
Dn Type= 3
Dn Slope=0.013
Boundary for River Rch & Prof#=Bitter Creek Tri,Reach-1         , 5
Up Type= 0
Dn Type= 3
Dn Slope=0.013
Boundary for River Rch & Prof#=Bitter Creek Tri,Reach-1         , 6
Up Type= 0
Dn Type= 3
Dn Slope=0.013
Boundary for River Rch & Prof#=Bitter Creek Tri,Reach-1         , 7
Up Type= 0
Dn Type= 3
Dn Slope=0.013
DSS Import GetInterval= 0
DSS Import GetPeak= 0
DSS Import FillOption= 0

--- Bitter Creek Trib6T2_1.g01 (geometry) ---

Geom Title=Existing Conditions
Program Version=4.10

River Reach=Bitter Creek Tri,Reach-1
Reach XY= 30
        1437205.        6799738.      1437153.59      6799691.39
      1437052.57      6799682.48      1436949.14      6799590.06
        1436705.        6799588.      1436697.24      6799644.21
      1436562.86      6799781.83      1436549.23      6799890.32
      1436511.14      6799935.83      1436496.84      6799994.05
      1436413.16      6800081.95      1436398.86      6800140.17
      1436356.36      6800197.65      1436353.62      6800578.34
      1436307.39      6800643.53      1436301.24      6800786.44
      1436261.12      6800835.82      1436250.81      6800886.26
      1436213.09      6800931.93      1436205.18      6800956.27
      1436207.25      6801082.06      1436254.32      6801151.92
      1436251.47      6801336.54      1436065.76      6801528.32
       1436048.9      6801590.19      1436009.19      6801639.74
      1435996.86      6801694.06      1435818.57      6801874.77
      1435799.29      6801940.35        1435755.        6801988.

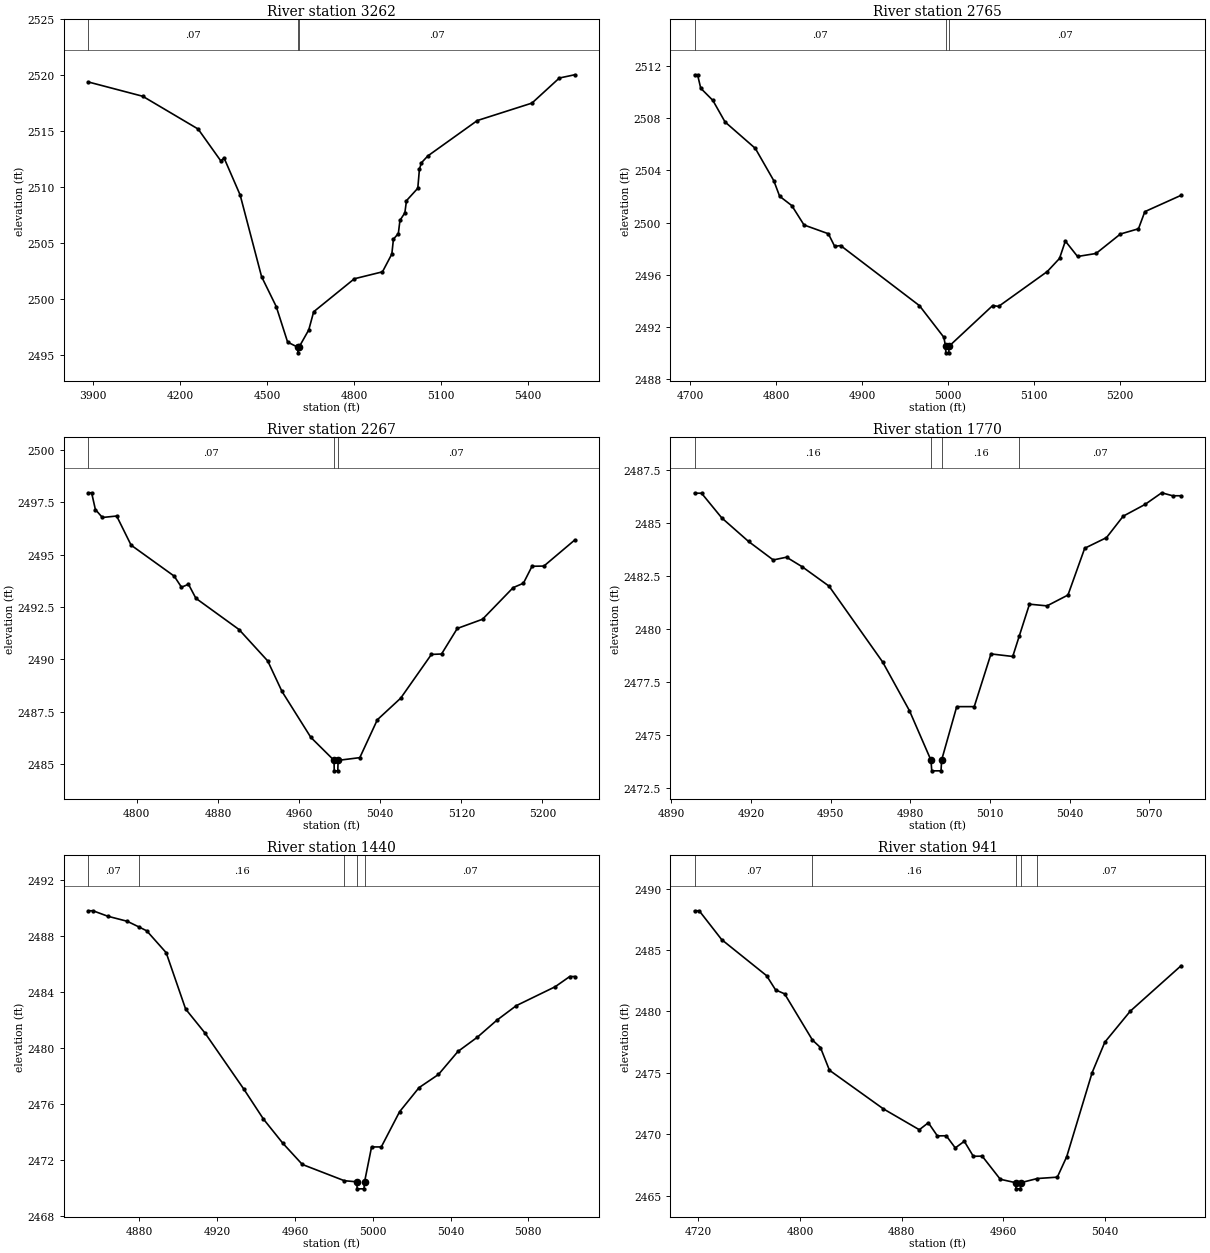
Type RM Length L Ch R = 1 ,3262    ,497,497,497
BEGIN DESCRIPTION:
Bitter Creek Trib6T2_1 6.0
END DESCRIPTION:
XS GIS Cut Line= 3
      1436655.02      6798688.04      1437149.16      6799690.02
      1437405.02      6800188.04
#Sta/Elev= 30
  3882.8 2519.39  4070.8 2518.11  4261.9 2515.18  4339.9 2512.34  4351.4 2512.59
  4406.8 2509.28  4480.6 2501.99  4531.1 2499.32  4570.4 2496.14  4605.5 2495.68
  4605.8 2495.18  4609.5 2495.68  4643.3 2497.23  4660.2 2498.85  4800.5  2501.8
  4897.4 2502.42  4929.7 2504.01  4935.2 2505.34  4952.1 2505.84  4957.7 2507.02
  4974.6 2507.69  4980.2 2508.78  5019.2 2509.89  5024.8 2511.59  5031.5 2512.16
  5053.9 2512.78  5224.4 2515.94  5412.8  2517.5  5507.2 2519.74  5559.9 2520.03
#Mann= 3 ,-1 , 0
  3882.8     .07       0  4605.5     .07       0  4609.5     .07       0
Bank Sta=4605.5,4609.5
XS Rating Curve= 0 ,0
Exp/Cntr=0.3,0.1

Type RM Length L Ch R = 1 ,2765    ,498,498,498
BEGIN DESCRIPTION:
Bitter Creek Trib6T2_1 5.0
END DESCRIPTION:
XS GIS Cut Line= 3
      1436505.02      6799388.02      1436705.48      6799604.16
        1436905.        6799788.
#Sta/Elev= 30
  4705.2  2511.3  4708.6  2511.3  4712.3 2510.27  4726.4 2509.34  4740.6 2507.69
  4775.8 2505.67  4797.3  2503.2  4804.1 2502.01  4818.3 2501.29  4832.5 2499.81
  4860.8 2499.14  4868.2 2498.17    4875 2498.24  4966.8 2493.64  4995.2 2491.22
  4997.2 2490.53  4997.5 2490.03    5001 2490.03  5001.2 2490.53  5052.1 2493.65
  5058.9 2493.58  5115.6 2496.25  5129.8 2497.25  5136.6 2498.58  5150.8  2497.4
  5172.3 2497.63  5200.7 2499.12  5221.7 2499.52  5229.1 2500.83  5271.3 2502.08
#Mann= 3 ,-1 , 0
  4705.2     .07       0  4997.2     .07       0  5001.2     .07       0
Bank Sta=4997.2,5001.2
XS Rating Curve= 0 ,0
Exp/Cntr=0.3,0.1

Type RM Length L Ch R = 1 ,2267    ,497,497,497
BEGIN DESCRIPTION:
Bitter Creek Trib6T2_1 4.0
END DESCRIPTION:
XS GIS Cut Line= 3
        1436305.        6799838.      1436475.31      6800018.13
      1436705.05      6799987.99
#Sta/Elev= 30
  4752.1 2497.95  4755.5 2497.95  4759.2 2497.15  4766.1 2496.77  4780.2 2496.84
  4794.4 2495.45  4836.9 2493.97  4844.1 2493.44    4851 2493.58  4858.3 2492.91
  4900.8 2491.42  4929.1 2489.92  4943.2 2488.46  4971.6 2486.27  4994.5 2485.17
  4994.7 2484.67  4998.2 2484.67  4998.5 2485.17  5019.9  2485.3  5037.2 2487.11
  5060.2 2488.14  5090.5 2490.23  5100.5 2490.25    5116 2491.47  5140.9 2491.91
  5171.1 2493.42  5181.2 2493.63  5189.7 2494.44  5201.4 2494.45  5231.7 2495.69
#Mann= 3 ,-1 , 0
  4752.1     .07       0  4994.5     .07       0  4998.5     .07       0
Bank Sta=4994.5,4998.5
XS Rating Curve= 0 ,0
Exp/Cntr=0.3,0.1

Type RM Length L Ch R = 1 ,1770    ,330,330,330
BEGIN DESCRIPTION:
Bitter Creek Trib6T2_1 3.0
END DESCRIPTION:
XS GIS Cut Line= 3
      1436254.96      6800488.01      1436355.04      6800473.02
      1436405.02      6800538.02
#Sta/Elev= 29
  4898.8 2486.39  4901.4 2486.39    4909 2485.23  4919.1 2484.12  4928.4 2483.25
  4933.4 2483.38  4939.3 2482.93  4949.4 2482.02  4969.6 2478.45  4979.7 2476.16
  4987.8 2473.83  4988.1 2473.33  4991.6 2473.33  4991.8 2473.83  4997.5 2476.35
  5004.1 2476.35  5010.4 2478.83  5018.6 2478.71  5021.1 2479.69  5024.9 2481.17
  5031.5 2481.09  5039.4  2481.6  5045.7  2483.8  5053.9  2484.3  5060.2 2485.31
  5068.4 2485.86  5074.7 2486.41  5078.8 2486.27    5082 2486.27
#Mann= 4 ,-1 , 0
  4898.8     .16       0  4987.8     .07       0  4991.8     .16       0
  5021.1     .07       0
Bank Sta=4987.8,4991.8
XS Rating Curve= 0 ,0
Exp/Cntr=0.3,0.1

Type RM Length L Ch R = 1 ,1440    ,499,499,499
BEGIN DESCRIPTION:
Bitter Creek Trib6T2_1 2.0
END DESCRIPTION:
XS GIS Cut Line= 3
      1436154.95        6800788.      1436301.24      6800786.44
      1436405.03        6800788.
#Sta/Elev= 30
  4853.7 2489.79  4856.2 2489.79  4863.8  2489.4  4873.8 2489.04  4879.6 2488.65
  4883.8 2488.36  4893.8  2486.8  4903.8 2482.78  4913.8 2481.06  4933.8 2477.05
  4943.8 2474.93  4953.8  2473.2  4963.8 2471.69  4985.4 2470.53  4991.8 2470.45
    4992 2469.95  4995.5 2469.95  4995.8 2470.45  4999.4 2472.94  5004.4 2472.94
  5013.8 2475.45  5023.8 2477.17  5033.8 2478.11  5043.8 2479.75  5053.8 2480.77
  5063.8 2481.98  5073.8 2483.02  5093.8 2484.37  5101.3  2485.1  5103.8  2485.1
#Mann= 5 ,-1 , 0
  4853.7     .07       0  4879.6     .16       0  4985.4     .07       0
  4991.8     .07       0  4995.8     .07       0
Bank Sta=4991.8,4995.8
XS Rating Curve= 0 ,0
Exp/Cntr=0.3,0.1

Type RM Length L Ch R = 1 ,941     ,441,441,441
BEGIN DESCRIPTION:
Bitter Creek Trib6T2_1 1.0
END DESCRIPTION:
XS GIS Cut Line= 3
      1436054.97      6801037.97      1436255.15        6801238.
      1436354.95        6801238.
#Sta/Elev= 30
    4717 2488.19  4720.6 2488.19  4738.3 2485.84  4773.6 2482.91  4780.7 2481.75
  4787.8 2481.43  4809.7 2477.67    4816 2477.06  4823.1 2475.21  4865.5 2472.07
  4893.8 2470.37  4900.9 2470.94    4908 2469.87    4915 2469.88  4922.1 2468.89
  4929.2 2469.43  4936.3 2468.21  4943.3 2468.22  4957.5 2466.34  4969.6 2466.06
  4969.9 2465.56  4973.4 2465.56  4973.6 2466.06  4986.7  2466.4  5002.4 2466.51
  5009.8 2468.18  5029.8 2475.02  5039.8  2477.5  5059.8 2480.02  5099.8 2483.72
#Mann= 5 ,-1 , 0
    4717     .07       0  4809.7     .16       0  4969.6     .07       0
  4973.6     .16       0  4986.7     .07       0
Bank Sta=4969.6,4973.6
XS Rating Curve= 0 ,0
Exp/Cntr=0.3,0.1

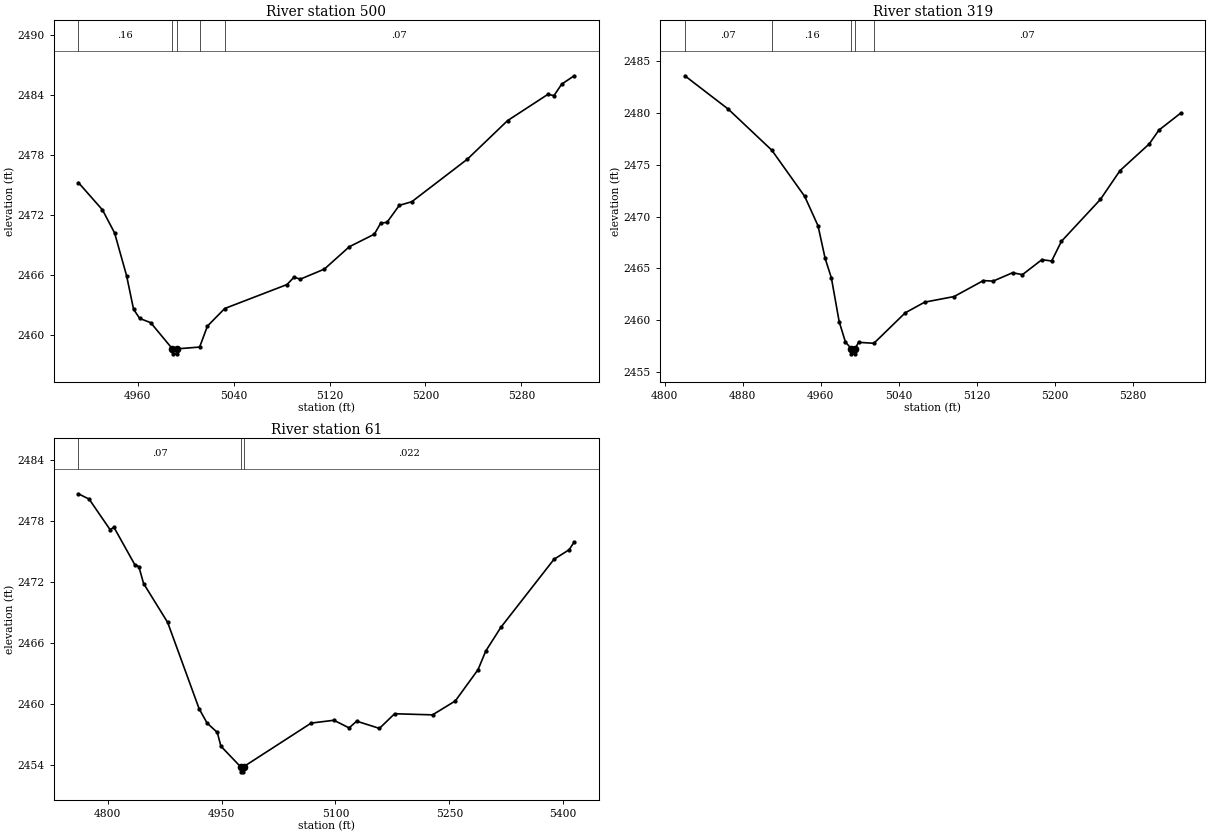
Type RM Length L Ch R = 1 ,500     ,181,181,181
BEGIN DESCRIPTION:
Bitter Creek Trib6T2_1 0.1
END DESCRIPTION:
XS GIS Cut Line= 3
      1435955.01        6801588.       1436043.9      6801597.55
      1436355.02      6801688.01
#Sta/Elev= 30
  4910.6 2475.25  4930.7 2472.51  4940.8  2470.2  4950.8 2465.91  4956.6 2462.56
  4961.7 2461.64  4970.9 2461.21    4989 2458.59  4989.3 2458.09  4992.8 2458.09
    4993 2458.59  5011.7 2458.77  5018.2 2460.87  5032.6 2462.63  5084.5 2465.03
  5090.4 2465.77  5095.6 2465.57  5115.7 2466.58  5136.5 2468.82  5157.4 2470.08
  5162.7 2471.19  5167.9 2471.26  5178.2 2472.97  5188.6 2473.33    5235  2477.6
  5268.5 2481.46    5302 2484.08  5307.2 2483.97  5313.6 2485.11    5324 2485.95
#Mann= 5 ,-1 , 0
  4910.6     .16       0    4989     .07       0    4993     .16       0
  5011.7     .16       0  5032.6     .07       0
Bank Sta=4989,4993
XS Rating Curve= 0 ,0
Exp/Cntr=0.3,0.1

Type RM Length L Ch R = 1 ,319     ,258,258,258
BEGIN DESCRIPTION:
Bitter Creek Trib6T2_1 4303
END DESCRIPTION:
XS GIS Cut Line= 3
      1435808.48      6801632.57      1435948.46      6801744.77
      1436277.21      6801750.64
#Sta/Elev= 30
  4820.6 2483.59  4865.1 2480.37  4909.8  2476.4  4943.5 2471.94  4957.1 2469.11
  4964.4 2465.96  4970.8 2464.08  4978.8 2459.85  4985.2 2457.89  4991.2 2457.25
  4991.4 2456.75  4994.9 2456.75  4995.2 2457.25  4998.6 2457.86  5014.4 2457.77
  5046.5 2460.71  5066.5 2461.74  5096.6 2462.28  5126.6 2463.82  5136.6 2463.77
  5156.6 2464.58  5166.6 2464.39  5186.6 2465.84  5196.6 2465.71  5206.6 2467.61
  5246.6 2471.66  5266.6 2474.43  5296.6 2477.01  5306.6 2478.35  5328.8 2479.98
#Mann= 5 ,-1 , 0
  4820.6     .07       0  4909.8     .16       0  4991.2     .07       0
  4995.2     .16       0  5014.4     .07       0
Bank Sta=4991.2,4995.2
XS Rating Curve= 0 ,0
Exp/Cntr=0.3,0.1

Type RM Length L Ch R = 1 ,61      ,0,0,0
BEGIN DESCRIPTION:
Bitter Creek Trib6T2_1 4301
END DESCRIPTION:
XS GIS Cut Line= 3
       1435726.9      6801715.88      1435797.06      6801944.14
      1436211.55      6801946.81
#Sta/Elev= 30
  4761.2 2480.64  4775.4 2480.11  4802.9 2477.12  4808.1 2477.34  4835.6 2473.66
  4840.9 2473.48  4847.1 2471.82  4878.8    2468  4920.3 2459.51  4930.8  2458.1
  4944.2 2457.19 4949.01 2455.83  4974.9 2453.81  4975.2 2453.31  4978.7 2453.31
  4978.9 2453.81  5067.9  2458.1  5097.9 2458.38  5117.9 2457.63  5127.9 2458.29
  5157.9 2457.58  5177.9 2459.02  5227.9 2458.91  5257.9 2460.28  5287.9 2463.36
  5297.9 2465.17  5317.9 2467.51  5387.9  2474.2  5407.9 2475.14  5414.5  2475.9
#Mann= 3 ,-1 , 0
  4761.2     .07       0  4974.9    .022       0  4978.9    .022       0
Bank Sta=4974.9,4978.9
XS Rating Curve= 0 ,0
Exp/Cntr=0.3,0.1

Chan Stop Cuts=-1
Use User Specified Reach Order=0
Composite Channel Slope=5