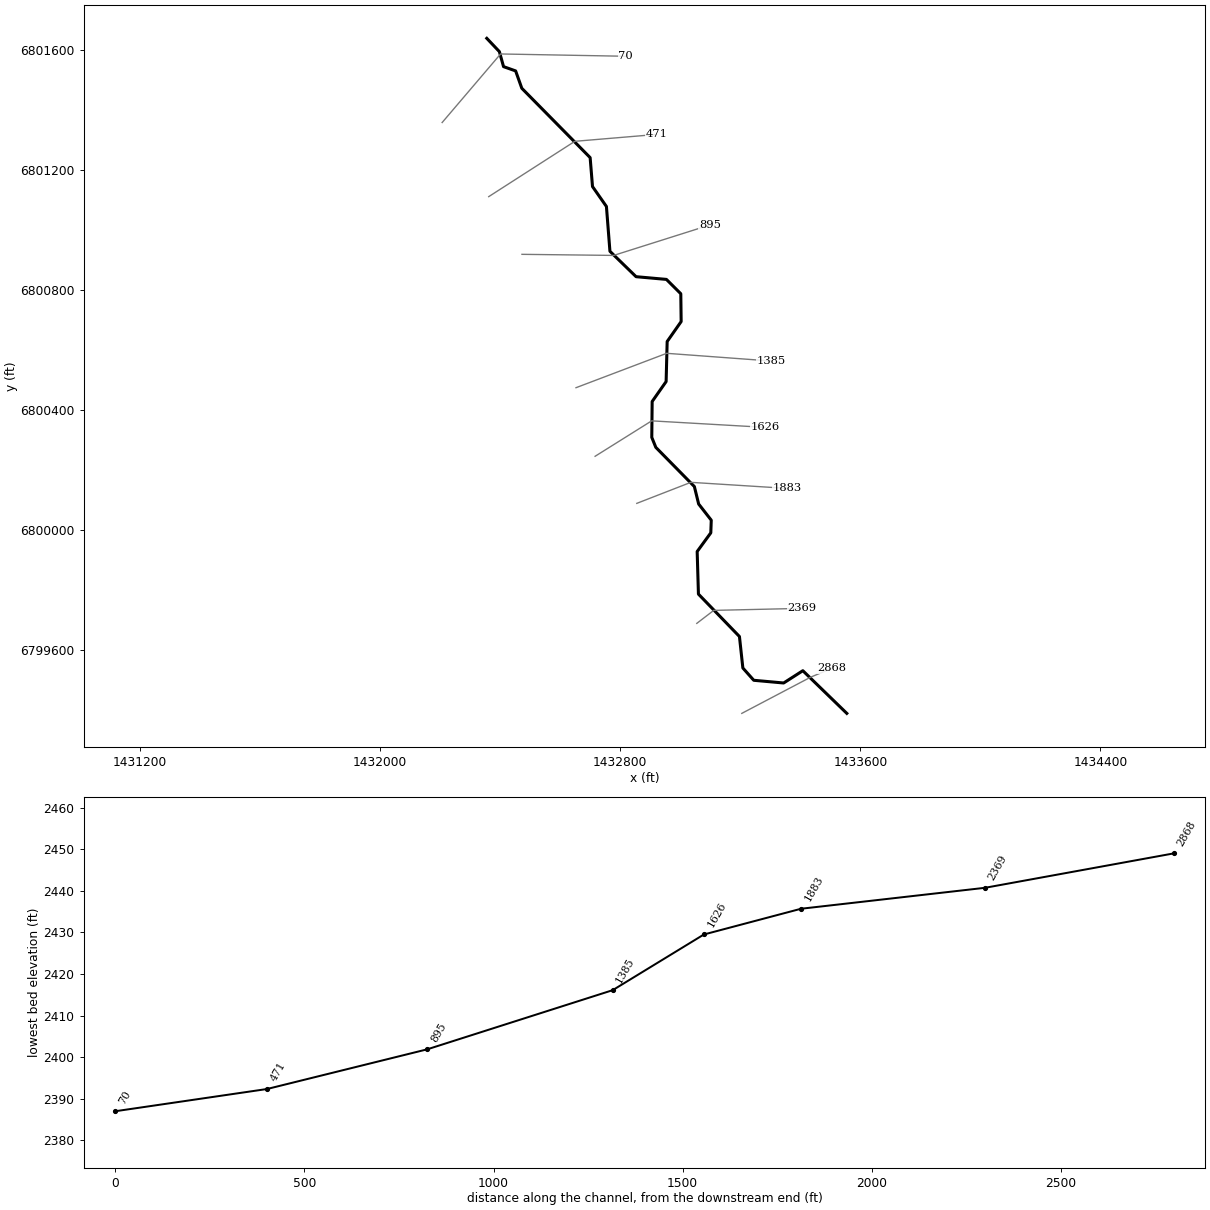
--- Bitter Creek Trib6T2_2.prj (project) ---

Proj Title=Bitter Creek Trib6T2_2 Base Level Engineering
Current Plan=p01
Default Exp/Contr=0.3,0.1
English Units
Geom File=g01
Flow File=f01
Plan File=p01
Y Axis Title=Elevation
X Axis Title(PF)=Main Channel Distance
X Axis Title(XS)=Station
BEGIN DESCRIPTION:
Bitter Creek Trib6T2_2
END DESCRIPTION:
DSS Export Rating Curves= 0
DSS Export Rating Curve Sorted= 0
DSS Export Volume Flow Curves= 0
DXF OffsetX= 0
DXF OffsetY= 0
DXF ScaleX= 1
DXF ScaleY= 10

--- Bitter Creek Trib6T2_2.p01 (plan) ---

Plan Title=Multiple Run
Short Identifier=Multiple
Geom File=g01
Flow File=f01
Subcritical Flow
K Sum by GR= 0
Std Step Tol= 0.01
Critical Tol= 0.01
Num of Std Step Trials= 20
Max Error Tol= 0.3
Flow Tol Ratio= 0.001
Split Flow NTrial= 30
Split Flow Tol= 0.02
Split Flow Ratio= 0.02
Log Output Level= 0
Friction Slope Method= 1
Unsteady Friction Slope Method= 2
Unsteady Bridges Friction Slope Method= 1
Parabolic Critical Depth
Global Vel Dist=  1 , 1 , 1
Global Log Level= 0
CheckData=True
Encroach Param= -1, 0, 0, 0
BEGIN DESCRIPTION:
Multiple Run
END DESCRIPTION:

--- Bitter Creek Trib6T2_2.f01 (steady flow) ---

Flow Title=Multiple
Program Version=4.10
Number of Profiles= 7
Profile Names=10-year,25-year,50-year,1pct_min,100-year,1pct_plu,500-year
River Rch & RM=Bitter Creek Tri,Reach-1         ,2868
     721    1064    1365     868    1732    3456    2827
Boundary for River Rch & Prof#=Bitter Creek Tri,Reach-1         , 1
Up Type= 0
Dn Type= 3
Dn Slope=0.013
Boundary for River Rch & Prof#=Bitter Creek Tri,Reach-1         , 2
Up Type= 0
Dn Type= 3
Dn Slope=0.013
Boundary for River Rch & Prof#=Bitter Creek Tri,Reach-1         , 3
Up Type= 0
Dn Type= 3
Dn Slope=0.013
Boundary for River Rch & Prof#=Bitter Creek Tri,Reach-1         , 4
Up Type= 0
Dn Type= 3
Dn Slope=0.013
Boundary for River Rch & Prof#=Bitter Creek Tri,Reach-1         , 5
Up Type= 0
Dn Type= 3
Dn Slope=0.013
Boundary for River Rch & Prof#=Bitter Creek Tri,Reach-1         , 6
Up Type= 0
Dn Type= 3
Dn Slope=0.013
Boundary for River Rch & Prof#=Bitter Creek Tri,Reach-1         , 7
Up Type= 0
Dn Type= 3
Dn Slope=0.013
DSS Import GetInterval= 0
DSS Import GetPeak= 0
DSS Import FillOption= 0

--- Bitter Creek Trib6T2_2.g01 (geometry) ---

Geom Title=Existing Conditions
Program Version=4.10

River Reach=Bitter Creek Tri,Reach-1
Reach XY= 30
        1433555.        6799388.      1433408.42      6799530.21
      1433344.51      6799489.27      1433244.84      6799498.28
      1433208.51      6799539.25      1433197.14      6799644.17
      1433060.45      6799785.55      1433056.23       6799927.5
      1433101.63      6799989.74       1433103.2      6800031.89
      1433061.18      6800085.81      1433046.86      6800144.06
      1432918.37      6800274.68      1432904.94      6800307.99
      1432906.21      6800427.49      1432952.73      6800493.94
      1432956.23      6800627.49      1433002.84      6800693.98
      1433001.64      6800786.75      1432953.75      6800834.49
      1432852.56      6800843.52      1432765.47      6800928.18
      1432753.77      6801077.49      1432707.36      6801143.98
      1432699.48      6801240.43      1432471.71      6801471.51
      1432451.14      6801529.39      1432410.84      6801543.67
      1432396.95      6801593.73        1432355.        6801638.

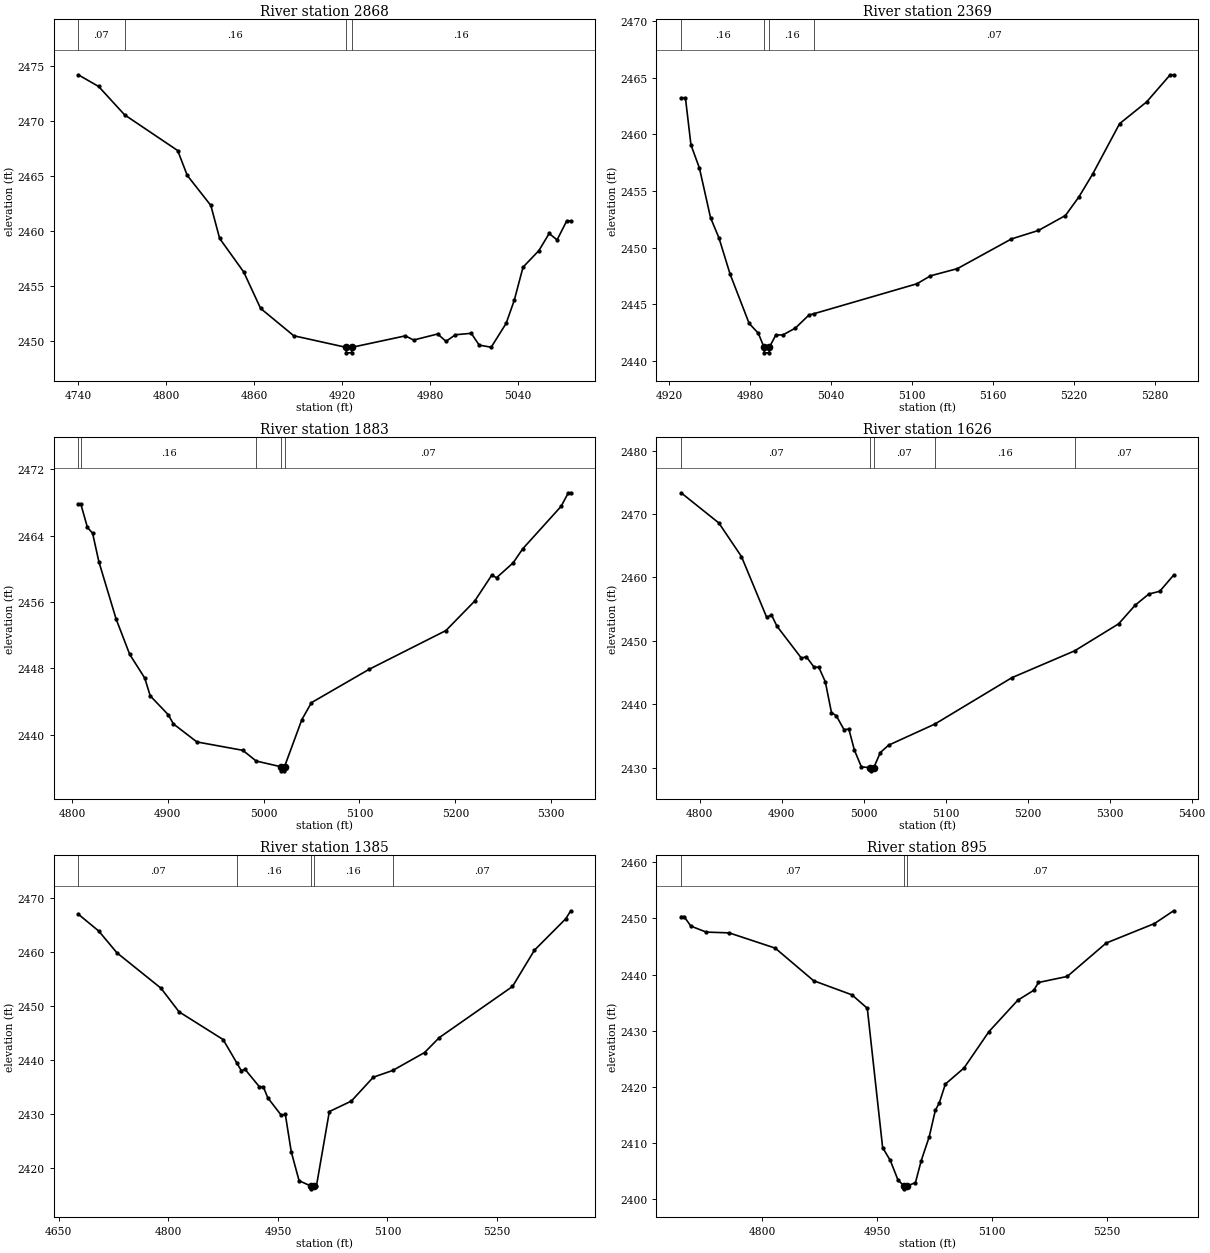
Type RM Length L Ch R = 1 ,2868    ,499,499,499
BEGIN DESCRIPTION:
Bitter Creek Trib6T2_2 5.0
END DESCRIPTION:
XS GIS Cut Line= 3
      1433204.99      6799387.99      1433435.02      6799508.96
      1433505.03      6799538.01
#Sta/Elev= 30
  4740.1 2474.18    4754 2473.12  4771.7 2470.55  4807.9 2467.31  4814.4 2465.06
  4830.5 2462.33  4836.5 2459.34  4852.9  2456.3  4864.4    2453    4887 2450.52
  4922.6 2449.47  4922.9 2448.97  4926.4 2448.97  4926.6 2449.47  4963.1 2450.51
  4968.7 2450.13  4985.1 2450.68  4990.8 2450.01  4997.2 2450.61    5008 2450.74
  5013.4 2449.67  5021.6 2449.48  5031.8 2451.65  5037.3 2453.73  5043.3 2456.74
  5054.1 2458.24  5061.1 2459.79  5066.5 2459.21  5073.1 2460.94  5075.8 2460.94
#Mann= 4 ,-1 , 0
  4740.1     .07       0  4771.7     .16       0  4922.6     .07       0
  4926.6     .16       0
Bank Sta=4922.6,4926.6
XS Rating Curve= 0 ,0
Exp/Cntr=0.3,0.1

Type RM Length L Ch R = 1 ,2369    ,486,486,486
BEGIN DESCRIPTION:
Bitter Creek Trib6T2_2 4.0
END DESCRIPTION:
XS GIS Cut Line= 3
      1433054.98      6799687.98      1433111.51      6799731.27
      1433405.03        6799738.
#Sta/Elev= 30
  4928.8 2463.23    4932 2463.23  4936.1 2459.07  4942.4 2457.01  4950.6 2452.64
  4956.9 2450.83  4965.1 2447.65  4979.2  2443.3    4986 2442.43  4990.2  2441.2
  4990.5  2440.7    4994  2440.7  4994.2  2441.2    4999 2442.28  5004.2 2442.28
  5013.5 2442.89  5023.5 2444.04  5027.6 2444.17  5103.5  2446.8  5113.5  2447.5
  5133.5 2448.14  5173.5 2450.76  5193.5 2451.51  5213.5 2452.83  5223.5 2454.48
  5233.6 2456.48  5253.6 2460.94  5273.6 2462.86  5291.1 2465.26  5293.6 2465.26
#Mann= 4 ,-1 , 0
  4928.8     .16       0  4990.2     .07       0  4994.2     .16       0
  5027.6     .07       0
Bank Sta=4990.2,4994.2
XS Rating Curve= 0 ,0
Exp/Cntr=0.3,0.1

Type RM Length L Ch R = 1 ,1883    ,257,257,257
BEGIN DESCRIPTION:
Bitter Creek Trib6T2_2 3.0
END DESCRIPTION:
XS GIS Cut Line= 3
      1432854.97      6800087.99      1433035.22      6800158.09
      1433354.99        6800138.
#Sta/Elev= 30
  4806.6 2467.83  4809.2 2467.83  4816.2 2464.98  4821.6 2464.28  4828.1 2460.86
  4846.1 2453.96  4860.3 2449.69    4876 2446.84  4881.7  2444.7  4900.5 2442.43
  4905.9 2441.32  4930.4 2439.15  4978.3 2438.14  4992.3 2436.85  5017.8 2436.17
  5018.1 2435.67  5021.6 2435.67  5021.8 2436.17  5039.9 2441.84  5049.9 2443.88
    5110 2447.89  5190.2 2452.56  5220.2 2456.11    5238 2459.23    5243 2458.92
  5260.3 2460.71  5270.3  2462.4  5310.4 2467.52  5317.9 2469.15  5320.4 2469.15
#Mann= 5 ,-1 , 0
  4806.6     .07       0  4809.2     .16       0  4992.3     .07       0
  5017.8     .07       0  5021.8     .07       0
Bank Sta=5017.8,5021.8
XS Rating Curve= 0 ,0
Exp/Cntr=0.3,0.1

Type RM Length L Ch R = 1 ,1626    ,241,241,241
BEGIN DESCRIPTION:
Bitter Creek Trib6T2_2 4182
END DESCRIPTION:
XS GIS Cut Line= 3
      1432716.02      6800244.89      1432904.59        6800363.
      1433281.87      6800341.37
#Sta/Elev= 30
  4777.5 2473.34  4823.5 2468.58  4851.1 2463.28  4881.8 2453.71  4887.7 2454.07
  4894.3 2452.31  4924.2 2447.25  4930.1 2447.49  4939.5 2445.85  4945.4 2445.82
  4953.3 2443.53  4960.8 2438.68  4966.7 2438.17  4976.1 2435.98    4982 2436.07
  4988.7 2432.78  4997.3  2430.1  5008.4 2429.98  5008.7 2429.48  5012.4 2429.98
  5020.4 2432.37  5030.5 2433.53  5086.9 2436.86  5180.7 2444.17  5257.3 2448.41
  5310.9 2452.67    5331  2455.6  5347.7 2457.37    5361  2457.8  5377.9 2460.34
#Mann= 5 ,-1 , 0
  4777.5     .07       0  5008.4     .07       0  5012.4     .07       0
  5086.9     .16       0  5257.3     .07       0
Bank Sta=5008.4,5012.4
XS Rating Curve= 0 ,0
Exp/Cntr=0.3,0.1

Type RM Length L Ch R = 1 ,1385    ,490,490,490
BEGIN DESCRIPTION:
Bitter Creek Trib6T2_2 2.0
END DESCRIPTION:
XS GIS Cut Line= 3
      1432652.37      6800473.52      1432954.67      6800588.14
      1433304.52      6800562.33
#Sta/Elev= 30
  4676.7 2466.94  4704.8 2463.81  4729.6 2459.79  4789.9 2453.24  4814.7 2448.86
    4875 2443.73  4893.9 2439.37  4899.8    2438  4905.2 2438.19  4924.6    2435
    4930 2435.01  4936.2 2432.94  4954.8 2429.68  4960.1 2429.93  4968.3 2422.94
    4979  2417.6  4995.5  2416.6  4995.8  2416.1  4999.5  2416.6  5002.7  2416.6
  5020.4  2430.4  5050.5 2432.34  5080.6 2436.76  5107.2 2438.01  5150.7 2441.32
  5170.8 2444.08  5271.1 2453.55  5301.1 2460.26    5344 2466.08  5350.8 2467.56
#Mann= 5 ,-1 , 0
  4676.7     .07       0  4893.9     .16       0  4995.5     .07       0
  4999.5     .16       0  5107.2     .07       0
Bank Sta=4995.5,4999.5
XS Rating Curve= 0 ,0
Exp/Cntr=0.3,0.1

Type RM Length L Ch R = 1 ,895     ,424,424,424
BEGIN DESCRIPTION:
Bitter Creek Trib6T2_2 1.0
END DESCRIPTION:
XS GIS Cut Line= 3
      1432472.26      6800918.05      1432777.84      6800914.42
      1433098.77      6801015.92
#Sta/Elev= 30
  4694.4 2450.31  4698.3 2450.31  4707.1 2448.62  4727.1 2447.55  4757.1 2447.41
  4817.1  2444.7  4867.2  2438.9  4917.2 2436.39  4937.2    2434  4957.2 2409.22
  4967.2 2406.93  4977.2 2403.46  4985.2 2402.39  4985.4 2401.89  4989.2 2402.39
    5000    2403  5007.5 2406.89    5018 2411.17  5025.9 2415.85  5031.1 2417.18
    5039 2420.52  5063.4 2423.39  5095.7 2429.83  5133.4 2435.43  5154.3  2437.2
  5160.4 2438.59  5197.9 2439.66  5248.7  2445.6  5311.7 2449.07  5336.6 2451.34
#Mann= 3 ,-1 , 0
  4694.4     .07       0  4985.2     .07       0  4989.2     .07       0
Bank Sta=4985.2,4989.2
XS Rating Curve= 0 ,0
Exp/Cntr=0.3,0.1

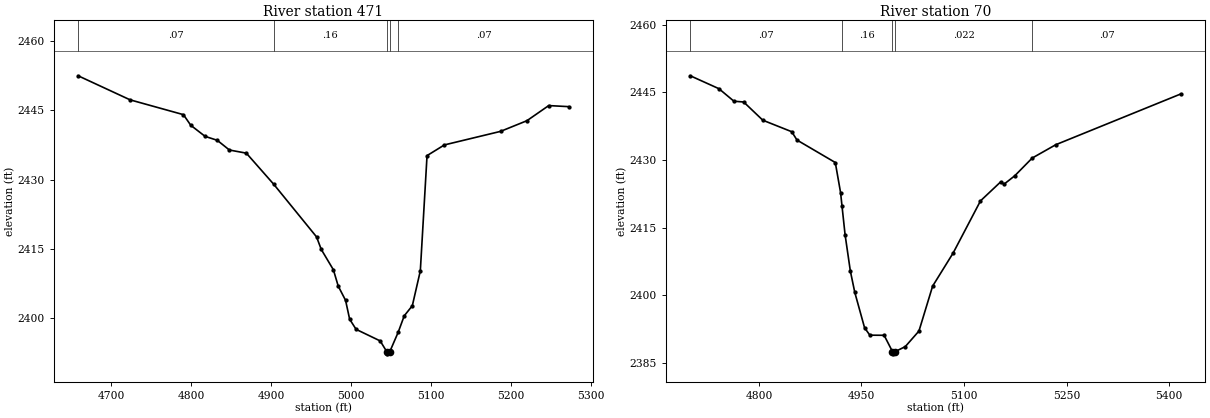
Type RM Length L Ch R = 1 ,471     ,401,401,401
BEGIN DESCRIPTION:
Bitter Creek Trib6T2_2 0.1
END DESCRIPTION:
XS GIS Cut Line= 3
      1432361.43      6801110.33      1432648.51      6801294.74
      1432919.95      6801317.57
#Sta/Elev= 30
  4658.8 2452.42  4723.8 2447.22  4790.5 2444.02  4799.7 2441.72  4817.6 2439.33
  4832.8 2438.48    4848 2436.38  4869.2  2435.7  4903.7 2428.93    4957 2417.61
  4962.9  2414.9  4978.1 2410.49  4984.1 2406.98  4993.3  2403.9  4998.4 2399.82
  5006.5 2397.63  5036.6 2395.13  5044.7 2392.84  5044.9 2392.34  5048.7 2392.84
  5059.1    2397  5066.7 2400.56  5076.8 2402.74  5086.8 2410.27  5095.2 2435.17
  5116.9 2437.48  5187.2 2440.41  5220.1 2442.71  5247.4 2445.98  5272.4 2445.75
#Mann= 5 ,-1 , 0
  4658.8     .07       0  4903.7     .16       0  5044.7     .07       0
  5048.7     .16       0  5059.1     .07       0
Bank Sta=5044.7,5048.7
XS Rating Curve= 0 ,0
Exp/Cntr=0.3,0.1

Type RM Length L Ch R = 1 ,70      ,0,0,0
BEGIN DESCRIPTION:
Bitter Creek Trib6T2_2 4303
END DESCRIPTION:
XS GIS Cut Line= 3
       1432206.2      6801357.34      1432400.97      6801585.91
       1432817.9      6801578.23
#Sta/Elev= 30
  4699.7 2448.64  4741.5 2445.78  4763.5    2443  4777.7 2442.83  4805.7 2438.79
    4848 2436.24  4855.7 2434.39  4911.7 2429.41  4919.4 2422.76  4921.5 2419.79
    4926 2413.41  4933.7 2405.36  4940.2 2400.62  4954.5 2392.78  4962.2 2391.14
  4983.1 2391.11  4995.3  2387.5  4995.6    2387  4999.3  2387.5    5014  2388.6
    5034 2392.05    5054 2402.01    5084 2409.35    5124 2420.91  5153.5 2425.12
  5158.5 2424.62  5174.1 2426.47  5199.6  2430.4  5234.1 2433.36    5417 2444.62
#Mann= 5 ,-1 , 0
  4699.7     .07       0  4921.5     .16       0  4995.3    .022       0
  4999.3    .022       0  5199.6     .07       0
Bank Sta=4995.3,4999.3
XS Rating Curve= 0 ,0
Exp/Cntr=0.3,0.1

Chan Stop Cuts=-1
Use User Specified Reach Order=0
Composite Channel Slope=5