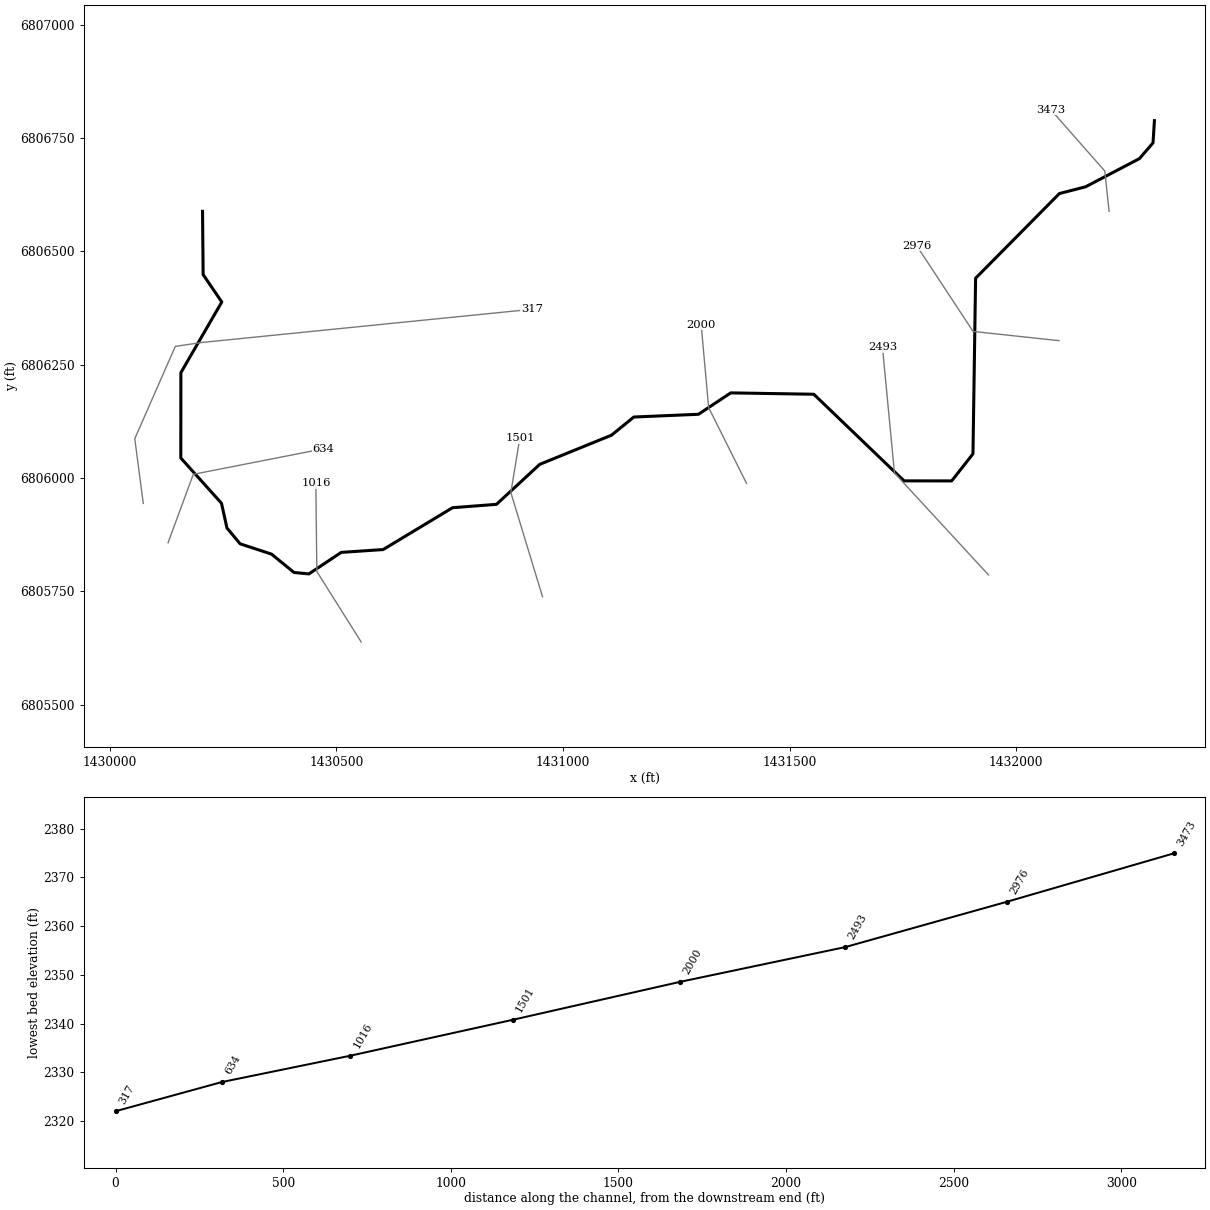
--- Bitter Creek Trib6T3.prj (project) ---

Proj Title=Bitter Creek Trib6T3 Base Level Engineering
Current Plan=p01
Default Exp/Contr=0.3,0.1
English Units
Geom File=g01
Flow File=f01
Plan File=p01
Y Axis Title=Elevation
X Axis Title(PF)=Main Channel Distance
X Axis Title(XS)=Station
BEGIN DESCRIPTION:
Bitter Creek Trib6T3
END DESCRIPTION:
DSS Export Rating Curves= 0
DSS Export Rating Curve Sorted= 0
DSS Export Volume Flow Curves= 0
DXF OffsetX= 0
DXF OffsetY= 0
DXF ScaleX= 1
DXF ScaleY= 10

--- Bitter Creek Trib6T3.p01 (plan) ---

Plan Title=Multiple Run
Short Identifier=Multiple
Geom File=g01
Flow File=f01
Subcritical Flow
K Sum by GR= 0
Std Step Tol= 0.01
Critical Tol= 0.01
Num of Std Step Trials= 20
Max Error Tol= 0.3
Flow Tol Ratio= 0.001
Split Flow NTrial= 30
Split Flow Tol= 0.02
Split Flow Ratio= 0.02
Log Output Level= 0
Friction Slope Method= 1
Unsteady Friction Slope Method= 2
Unsteady Bridges Friction Slope Method= 1
Parabolic Critical Depth
Global Vel Dist=  1 , 1 , 1
Global Log Level= 0
CheckData=True
Encroach Param= -1, 0, 0, 0
BEGIN DESCRIPTION:
Multiple Run
END DESCRIPTION:

--- Bitter Creek Trib6T3.f01 (steady flow) ---

Flow Title=Multiple
Program Version=4.10
Number of Profiles= 7
Profile Names=10-year,25-year,50-year,1pct_min,100-year,1pct_plu,500-year
River Rch & RM=Bitter Creek Tri,Reach-1         ,3473
     322     456     570     354     706    1408    1096
River Rch & RM=Bitter Creek Tri,Reach-1         ,2493
     360     516     648     405     808    1613    1273
Boundary for River Rch & Prof#=Bitter Creek Tri,Reach-1         , 1
Up Type= 0
Dn Type= 3
Dn Slope=0.019
Boundary for River Rch & Prof#=Bitter Creek Tri,Reach-1         , 2
Up Type= 0
Dn Type= 3
Dn Slope=0.019
Boundary for River Rch & Prof#=Bitter Creek Tri,Reach-1         , 3
Up Type= 0
Dn Type= 3
Dn Slope=0.019
Boundary for River Rch & Prof#=Bitter Creek Tri,Reach-1         , 4
Up Type= 0
Dn Type= 3
Dn Slope=0.019
Boundary for River Rch & Prof#=Bitter Creek Tri,Reach-1         , 5
Up Type= 0
Dn Type= 3
Dn Slope=0.019
Boundary for River Rch & Prof#=Bitter Creek Tri,Reach-1         , 6
Up Type= 0
Dn Type= 3
Dn Slope=0.019
Boundary for River Rch & Prof#=Bitter Creek Tri,Reach-1         , 7
Up Type= 0
Dn Type= 3
Dn Slope=0.019
DSS Import GetInterval= 0
DSS Import GetPeak= 0
DSS Import FillOption= 0

--- Bitter Creek Trib6T3.g01 (geometry) ---

Geom Title=Existing Conditions
Program Version=4.10

River Reach=Bitter Creek Tri,Reach-1
Reach XY= 30
        1432305.        6806788.      1432301.86      6806739.03
      1432272.04      6806704.37      1432153.27      6806642.19
      1432095.32      6806627.24      1431910.46      6806440.45
      1431904.68      6806053.02      1431857.71      6805993.28
      1431752.58      6805993.39      1431553.54      6806184.47
      1431370.22      6806187.48      1431299.06      6806140.27
      1431156.56      6806134.24      1431107.18      6806094.12
      1430948.95      6806029.84       1430853.5      6805941.62
      1430756.59      6805934.17      1430603.42      6805841.83
      1430510.97      6805835.62       1430439.6      6805788.08
      1430406.72      6805791.34      1430357.16      6805831.81
      1430287.95      6805854.48      1430258.89      6805889.43
      1430246.81      6805944.02      1430157.06      6806043.86
      1430157.24      6806232.07      1430247.48      6806387.99
      1430206.34      6806448.41        1430205.        6806588.

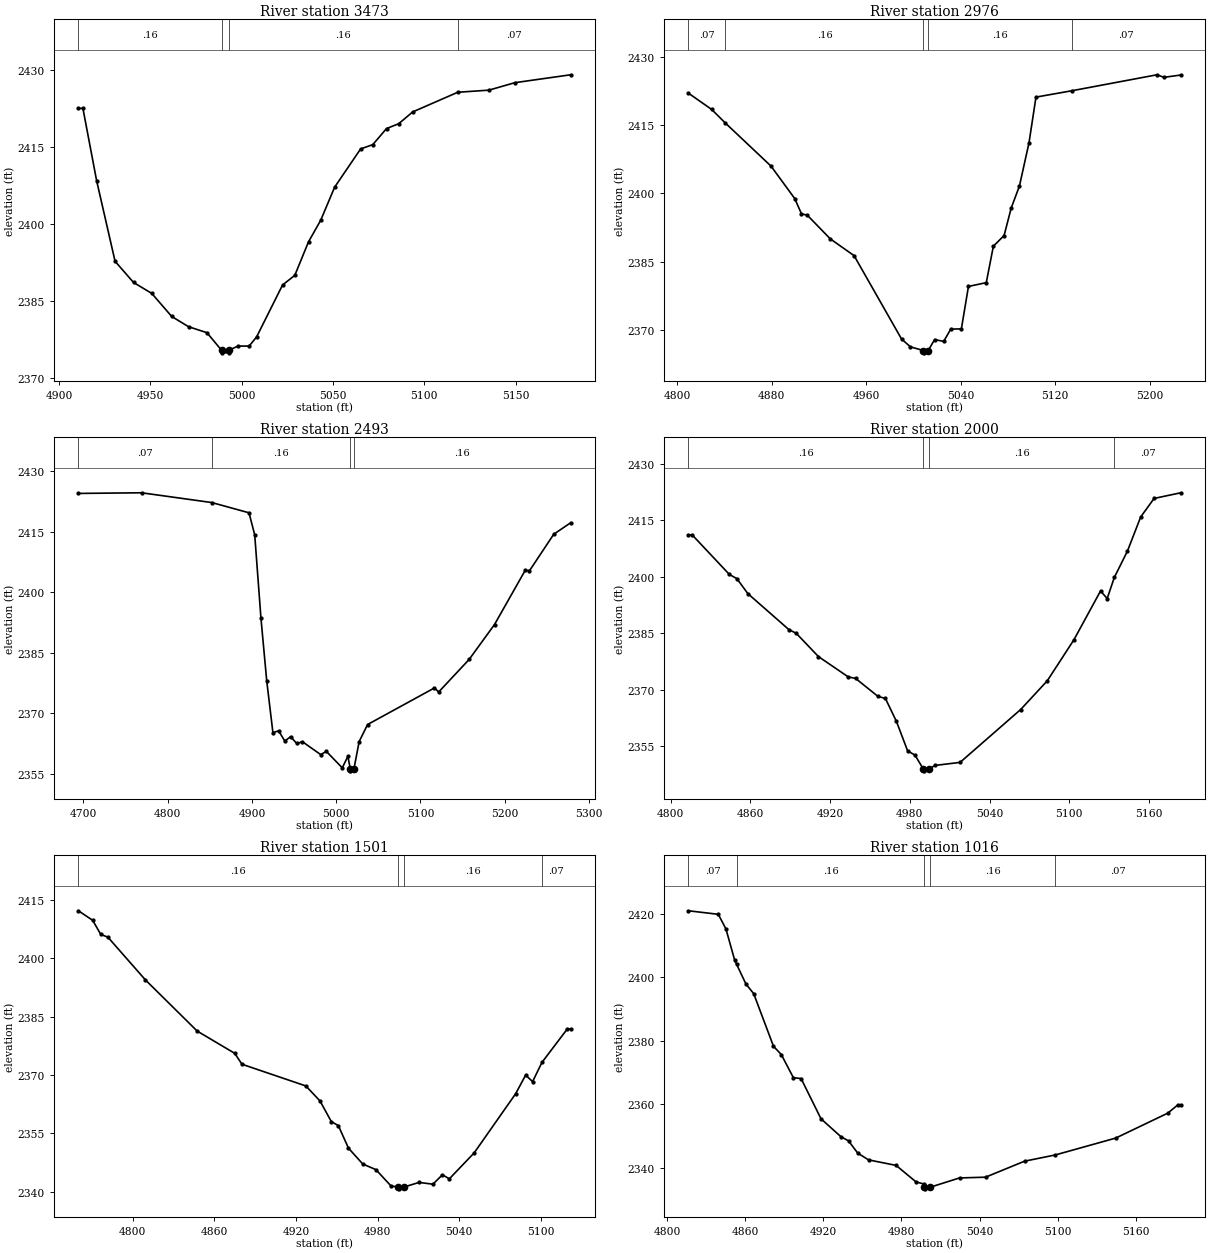
Type RM Length L Ch R = 1 ,3473    ,497,497,497
BEGIN DESCRIPTION:
Bitter Creek Trib6T3 5.0
END DESCRIPTION:
XS GIS Cut Line= 3
        1432205.      6806588.02      1432195.46      6806676.91
      1432076.47       6806812.1
#Sta/Elev= 30
  4910.6 2422.61  4913.1 2422.61  4920.6 2408.51  4930.7 2392.78  4940.8 2388.65
  4950.8 2386.51  4961.7 2382.02  4970.9 2380.02    4981 2378.85    4989 2375.42
  4989.3 2374.92  4992.8 2374.92    4993 2375.42    4998 2376.24  5004.1 2376.24
  5008.2 2378.04  5022.4 2388.16  5029.1 2390.04  5036.6 2396.58  5043.3  2400.8
  5050.9 2407.24  5065.1 2414.69  5071.8 2415.54  5079.3 2418.67    5086 2419.62
  5093.6 2421.91  5118.3 2425.75  5135.3 2426.16  5149.6 2427.62  5180.1 2429.16
#Mann= 4 ,-1 , 0
  4910.6     .16       0    4989     .07       0    4993     .16       0
  5118.3     .07       0
Bank Sta=4989,4993
XS Rating Curve= 0 ,0
Exp/Cntr=0.3,0.1

Type RM Length L Ch R = 1 ,2976    ,483,483,483
BEGIN DESCRIPTION:
Bitter Creek Trib6T3 4.0
END DESCRIPTION:
XS GIS Cut Line= 3
      1432094.48      6806302.73      1431904.96      6806323.02
      1431780.43      6806512.22
#Sta/Elev= 30
  4809.4 2421.96    4829  2418.4  4840.7  2415.4  4879.3 2405.97  4899.4 2398.85
  4905.1 2395.52  4910.2 2395.16  4929.6 2389.99  4949.7 2386.32  4989.9 2368.04
  4997.4 2366.32  5008.5  2365.5  5008.7    2365  5012.5  2365.5  5017.9 2367.91
  5025.6 2367.51  5031.6  2370.2  5040.6 2370.26  5046.6 2379.57  5061.7  2380.4
  5067.7 2388.39  5076.8 2390.74  5082.8 2396.76  5089.8  2401.6  5097.9 2411.09
  5103.8  2421.1  5134.3  2422.5  5206.3    2426  5212.3 2425.44  5226.5 2425.95
#Mann= 5 ,-1 , 0
  4809.4     .07       0  4840.7     .16       0  5008.5     .07       0
  5012.5     .16       0  5134.3     .07       0
Bank Sta=5008.5,5012.5
XS Rating Curve= 0 ,0
Exp/Cntr=0.3,0.1

Type RM Length L Ch R = 1 ,2493    ,493,493,493
BEGIN DESCRIPTION:
Bitter Creek Trib6T3 3.0
END DESCRIPTION:
XS GIS Cut Line= 3
      1431938.98       6805785.8      1431731.48      6806010.84
        1431705.      6806287.98
#Sta/Elev= 30
  4693.9 2424.44  4768.9  2424.6  4852.3 2422.18  4896.5 2419.64  4903.3 2414.17
  4910.7 2393.51  4917.5 2378.07  4924.9 2365.15  4931.7  2365.6    4939 2363.06
  4945.9 2364.15  4953.2 2362.46    4960 2362.89  4981.6 2359.71  4988.4 2360.49
  5007.2 2356.43  5013.9 2359.25  5016.8 2356.18    5017 2355.68  5021.1 2356.18
  5027.3 2362.94  5037.3 2367.16  5116.7 2376.23  5121.7 2375.22  5157.9  2383.3
    5188 2391.95  5224.5  2405.4  5229.5 2405.27  5258.3 2414.32  5278.4 2417.17
#Mann= 4 ,-1 , 0
  4693.9     .07       0  4852.3     .16       0  5016.8     .07       0
  5021.1     .16       0
Bank Sta=5016.8,5021.1
XS Rating Curve= 0 ,0
Exp/Cntr=0.3,0.1

Type RM Length L Ch R = 1 ,2000    ,499,499,499
BEGIN DESCRIPTION:
Bitter Creek Trib6T3 2.0
END DESCRIPTION:
XS GIS Cut Line= 3
      1431405.01      6805987.99      1431321.57       6806154.9
        1431305.      6806338.05
#Sta/Elev= 30
  4813.4 2411.08  4816.2 2411.08  4844.2 2400.59  4849.8  2399.5  4858.1 2395.51
  4888.9    2386  4894.5    2385  4911.2 2378.83  4933.6 2373.45  4939.2 2373.03
    4956 2368.27  4961.6 2367.73  4969.9 2361.64  4978.3 2353.85  4983.9 2352.69
  4990.1 2349.04  4990.4 2348.54  4994.5 2349.04  4998.9 2349.97  5017.8 2350.78
  5063.4  2364.8  5083.4  2372.4  5103.5  2383.3  5123.5 2396.22  5128.5 2394.22
  5133.9 2399.83  5143.7 2406.76  5153.7 2415.83  5163.8 2420.75  5183.9 2422.25
#Mann= 4 ,-1 , 0
  4813.4     .16       0  4990.1     .07       0  4994.5     .16       0
  5133.9     .07       0
Bank Sta=4990.1,4994.5
XS Rating Curve= 0 ,0
Exp/Cntr=0.3,0.1

Type RM Length L Ch R = 1 ,1501    ,485,485,485
BEGIN DESCRIPTION:
Bitter Creek Trib6T3 1.0
END DESCRIPTION:
XS GIS Cut Line= 3
      1430955.01      6805737.98      1430885.17      6805967.59
        1430905.      6806087.97
#Sta/Elev= 30
    4760 2412.18  4770.5 2409.75  4776.5  2406.1  4781.7 2405.41  4809.3 2394.43
  4847.4 2381.27    4875 2375.56  4880.3 2372.76  4927.3 2367.18  4937.7 2363.32
    4946 2358.03  4951.2 2356.99  4958.6 2351.21  4969.1 2347.14  4978.8 2345.68
    4990 2341.45  4995.4 2341.25  4995.7 2340.75  4999.8 2341.25  5010.5  2342.4
  5020.7 2341.94  5027.7 2344.36  5032.8 2343.32  5051.1 2350.01  5081.5 2365.16
  5088.9 2369.97    5094 2368.29  5100.9 2373.24  5119.5 2381.81    5122 2381.81
#Mann= 4 ,-1 , 0
    4760     .16       0  4995.4     .07       0  4999.8     .16       0
  5100.9     .07       0
Bank Sta=4995.4,4999.8
XS Rating Curve= 0 ,0
Exp/Cntr=0.3,0.1

Type RM Length L Ch R = 1 ,1016    ,382,382,382
BEGIN DESCRIPTION:
Bitter Creek Trib6T3 0.1
END DESCRIPTION:
XS GIS Cut Line= 3
        1430555.        6805638.      1430457.18      6805793.37
        1430455.      6805987.96
#Sta/Elev= 30
  4816.4 2420.91  4839.3  2419.8  4845.2 2415.17  4851.9 2405.35  4853.4 2404.05
  4860.5 2397.88  4866.5 2394.82  4881.7 2378.26  4887.7 2375.65    4897 2368.35
  4902.9  2368.1  4918.2 2355.42  4933.5 2349.79  4939.4 2348.45  4946.4 2344.63
  4954.7 2342.49  4975.9 2340.75  4991.2 2335.55  4997.1 2334.91  4997.6 2333.87
  4997.9 2333.37    5002 2333.87  5024.6  2336.8  5044.6 2337.04  5074.6 2342.08
  5098.2 2344.04  5144.6 2349.35  5184.6  2357.2  5192.1 2359.73  5194.6 2359.73
#Mann= 5 ,-1 , 0
  4816.4     .07       0  4853.4     .16       0  4997.6     .07       0
    5002     .16       0  5098.2     .07       0
Bank Sta=4997.6,5002
XS Rating Curve= 0 ,0
Exp/Cntr=0.3,0.1

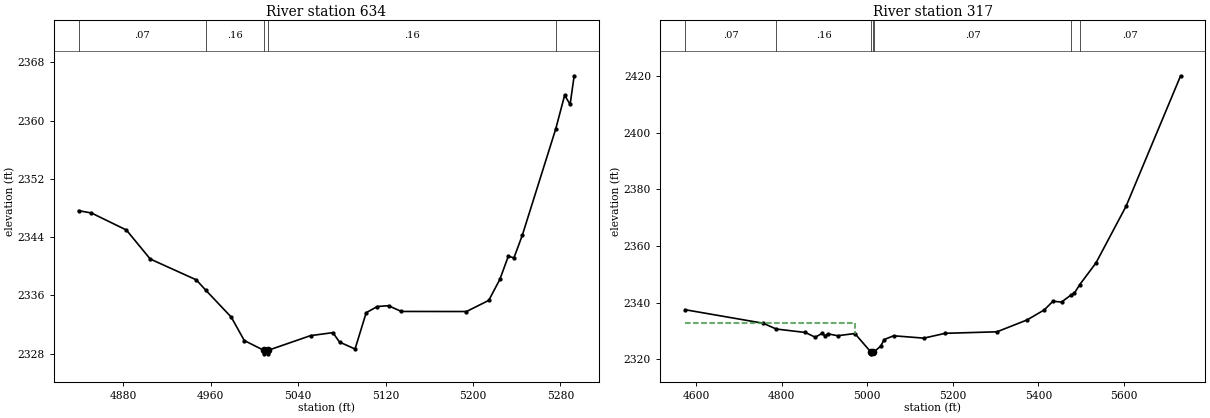
Type RM Length L Ch R = 1 ,634     ,317,317,317
BEGIN DESCRIPTION:
Bitter Creek Trib6T3 4306
END DESCRIPTION:
XS GIS Cut Line= 3
        1430129.      6805856.94      1430184.58      6806007.83
      1430471.62      6806064.09
#Sta/Elev= 30
  4839.2 2347.64    4851 2347.32    4883 2344.98  4904.8    2341  4946.9 2338.14
  4955.4 2336.75  4978.9 2333.02  4990.8 2329.81  5008.4 2328.48  5008.7 2327.98
  5012.5 2327.98  5012.9 2328.48  5051.4 2330.48  5071.8 2330.89  5077.9  2329.6
  5092.1 2328.64  5102.3 2333.63  5112.5 2334.48  5122.7 2334.59  5134.4  2333.8
    5194 2333.79  5214.4 2335.32  5224.6 2338.23  5232.3 2341.39  5237.4 2341.15
    5245 2344.23  5275.6 2358.84  5283.8 2363.49  5288.8 2362.22  5292.5 2366.16
#Mann= 5 ,-1 , 0
  4839.2     .07       0  4955.4     .16       0  5008.4     .07       0
  5012.9     .16       0  5275.6     .07       0
Bank Sta=5008.4,5012.9
XS Rating Curve= 0 ,0
Exp/Cntr=0.3,0.1

Type RM Length L Ch R = 1 ,317     ,0,0,0
BEGIN DESCRIPTION:
Bitter Creek Trib6T3 4307
END DESCRIPTION:
XS GIS Cut Line= 5
      1430074.29      6805943.63      1430055.52      6806086.43
      1430144.96      6806290.07      1430203.38      6806298.71
      1430931.81      6806371.95
#Sta/Elev= 30
  4574.5 2337.56  4756.5  2332.8  4787.8 2330.74  4855.4 2329.53  4878.7 2327.86
    4895 2329.23  4902.1 2328.23  4907.6 2329.07  4930.9 2328.38  4971.3 2329.15
  5009.4 2322.49  5009.8 2321.99  5013.9 2322.49  5015.2 2322.56  5031.8 2324.74
  5039.8 2327.04  5061.9 2328.36  5132.3 2327.53  5182.5 2329.23  5303.1 2329.76
  5373.5 2333.95  5413.7 2337.49  5433.8 2340.54  5453.9 2340.25    5477 2342.84
  5484.1 2343.42  5496.3 2346.37  5534.3 2354.04  5604.7 2374.06  5732.1 2420.06
#Mann= 7 ,-1 , 0
  4574.5     .07       0  4787.8     .16       0  5009.4     .07       0
  5013.9     .16       0  5015.2     .07       0    5477     .16       0
  5496.3     .07       0
#XS Ineff= 2 , 0
         4971.38 2332.82
Permanent Ineff=
       F       F
Bank Sta=5009.4,5013.9
XS Rating Curve= 0 ,0
Exp/Cntr=0.3,0.1

Chan Stop Cuts=-1
Use User Specified Reach Order=0
Composite Channel Slope=5