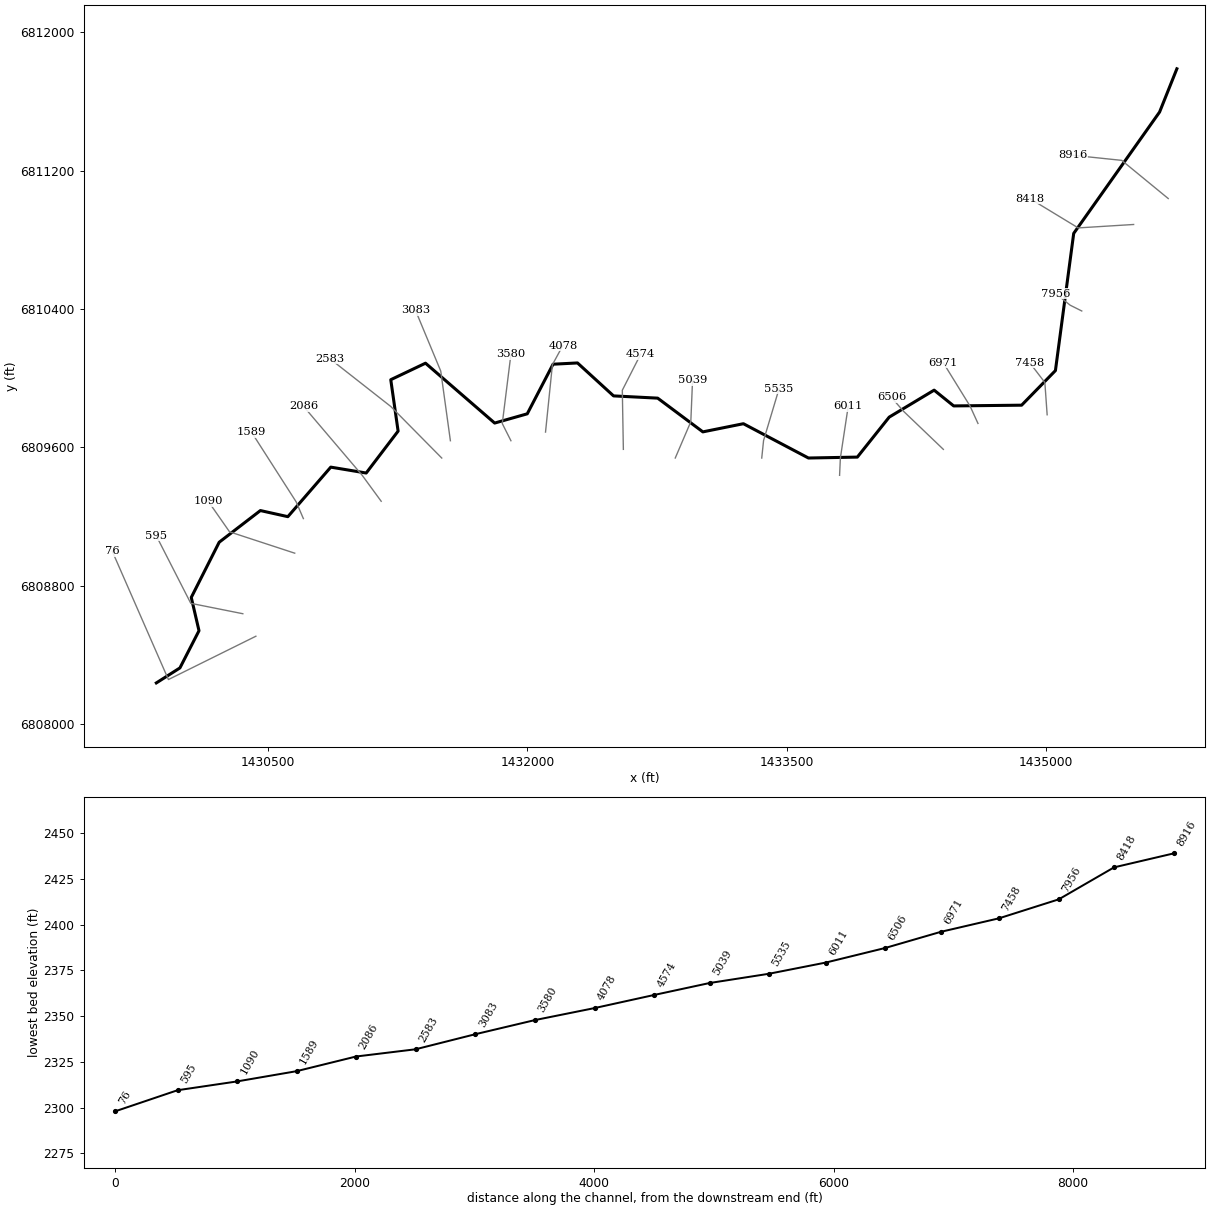
--- Bitter Creek Trib6T4.prj (project) ---

Proj Title=Bitter Creek Trib6T4 Base Level Engineering
Current Plan=p01
Default Exp/Contr=0.3,0.1
English Units
Geom File=g01
Flow File=f01
Plan File=p01
Y Axis Title=Elevation
X Axis Title(PF)=Main Channel Distance
X Axis Title(XS)=Station
BEGIN DESCRIPTION:
Bitter Creek Trib6T4
END DESCRIPTION:
DSS Export Rating Curves= 0
DSS Export Rating Curve Sorted= 0
DSS Export Volume Flow Curves= 0
DXF OffsetX= 0
DXF OffsetY= 0
DXF ScaleX= 1
DXF ScaleY= 10

--- Bitter Creek Trib6T4.p01 (plan) ---

Plan Title=Multiple Run
Short Identifier=Multiple
Geom File=g01
Flow File=f01
Subcritical Flow
K Sum by GR= 0
Std Step Tol= 0.01
Critical Tol= 0.01
Num of Std Step Trials= 20
Max Error Tol= 0.3
Flow Tol Ratio= 0.001
Split Flow NTrial= 30
Split Flow Tol= 0.02
Split Flow Ratio= 0.02
Log Output Level= 0
Friction Slope Method= 1
Unsteady Friction Slope Method= 2
Unsteady Bridges Friction Slope Method= 1
Parabolic Critical Depth
Global Vel Dist=  1 , 1 , 1
Global Log Level= 0
CheckData=True
Encroach Param= -1, 0, 0, 0
BEGIN DESCRIPTION:
Multiple Run
END DESCRIPTION:

--- Bitter Creek Trib6T4.f01 (steady flow) ---

Flow Title=Multiple
Number of Profiles=7
Profile Names=10-year,25-year,50-year,1pct_min,100-year,1pct_plu,500-year
River Rch & RM= Bitter Creek Tri,Reach-1,8916
     228     314     384     234     466     930     695
River Rch & RM= Bitter Creek Tri,Reach-1,8418
     366     520     649     403     804    1605    1250
River Rch & RM= Bitter Creek Tri,Reach-1,7458
     586     863    1104     702    1401    2794    2282
Boundary for River Rch & Prof#=Bitter Creek Tri,Reach-1,1
Up Type=0
Dn Type=3
Dn Slope=0.005
Boundary for River Rch & Prof#=Bitter Creek Tri,Reach-1,2
Up Type=0
Dn Type=3
Dn Slope=0.005
Boundary for River Rch & Prof#=Bitter Creek Tri,Reach-1,3
Up Type=0
Dn Type=3
Dn Slope=0.005
Boundary for River Rch & Prof#=Bitter Creek Tri,Reach-1,4
Up Type=0
Dn Type=3
Dn Slope=0.005
Boundary for River Rch & Prof#=Bitter Creek Tri,Reach-1,5
Up Type=0
Dn Type=3
Dn Slope=0.005
Boundary for River Rch & Prof#=Bitter Creek Tri,Reach-1,6
Up Type=0
Dn Type=3
Dn Slope=0.005
Boundary for River Rch & Prof#=Bitter Creek Tri,Reach-1,7
Up Type=0
Dn Type=3
Dn Slope=0.005

--- Bitter Creek Trib6T4.g01 (geometry) ---

Geom Title=Existing Conditions

River Reach=Bitter Creek Tri,Reach-1
Reach XY= 30
      1435755.00      6811788.00      1435655.00      6811538.00
      1435158.54      6810836.54      1435052.83      6810043.44
      1434857.45      6809843.46      1434464.59      6809839.22
      1434351.67      6809930.39      1434091.78      6809774.38
      1433907.70      6809543.36      1433625.03      6809538.07
      1433248.96      6809736.37      1433014.59      6809689.19
      1432753.42      6809884.18      1432498.27      6809897.15
      1432289.83      6810087.64      1432148.48      6810080.33
      1431999.39      6809793.59      1431810.97      6809740.14
      1431411.17      6810086.23      1431210.34      6809990.73
      1431252.74      6809693.56      1431068.30      6809451.34
      1430863.48      6809485.37      1430615.36      6809199.02
      1430456.59      6809234.32      1430218.40      6809051.31
      1430056.97      6808732.11      1430101.66      6808539.72
      1429991.40      6808324.76      1429855.00      6808238.00

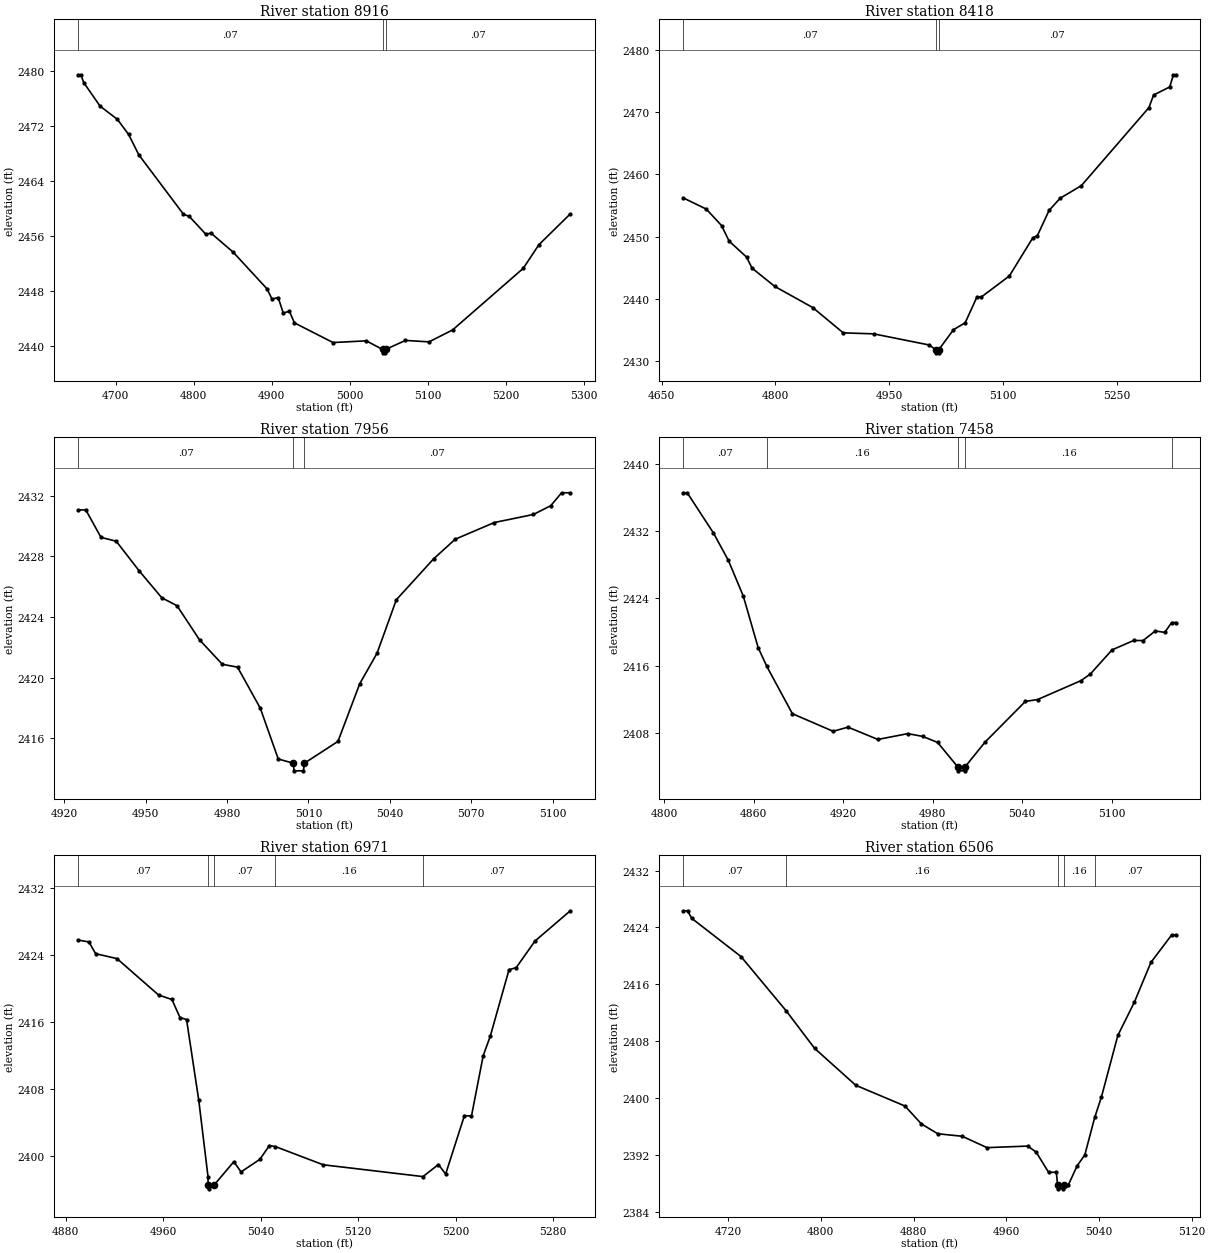
Type RM Length L Ch R = 1,8916,498,498,498
BEGIN DESCRIPTION:
Bitter Creek Trib6T4 17.0
END DESCRIPTION:
XS GIS Cut Line= 3
      1435705.02      6811037.99      1435435.95      6811258.69
      1435154.98      6811288.00
#Sta/Elev= 30
  4652.0 2479.51  4655.3 2479.51  4659.2 2478.35  4680.0 2474.94  4702.2 2473.01
  4716.6 2470.81  4729.6 2467.85  4786.9 2459.17  4794.3 2458.86  4815.6 2456.25
  4822.1 2456.43  4850.8 2453.62  4893.9 2448.30  4900.3 2446.81  4908.2 2447.03
  4914.7 2444.78  4922.6 2445.03  4929.0 2443.34  4978.5 2440.47  5021.1 2440.72
  5041.9 2439.47  5042.1 2438.97  5045.6 2438.97  5045.9 2439.47  5071.3 2440.78
  5101.5 2440.57  5131.7 2442.31  5222.2 2451.29  5242.3 2454.74  5282.5 2459.23
#Mann=3,-1,0
  4652.0    0.07       0  5041.9    0.07       0  5045.9    0.07       0
Bank Sta=5041.9,5045.9
Exp/Cntr=0.3,0.1

Type RM Length L Ch R = 1,8418,462,462,462
BEGIN DESCRIPTION:
Bitter Creek Trib6T4 16.0
END DESCRIPTION:
XS GIS Cut Line= 3
      1435505.00      6810888.00      1435184.51      6810868.20
      1434905.04      6811037.98
#Sta/Elev= 30
  4678.9 2456.21  4709.0 2454.43  4729.0 2451.79  4739.0 2449.29  4762.0 2446.72
  4769.1 2444.96  4799.1 2442.01  4849.2 2438.61  4889.3 2434.55  4929.4 2434.39
  5002.6 2432.60  5011.1 2431.84  5011.4 2431.34  5014.9 2431.34  5015.1 2431.84
  5034.5 2435.06  5049.9 2436.17  5065.4 2440.32  5071.3 2440.32  5108.1 2443.69
  5139.0 2449.83  5144.9 2450.15  5160.4 2454.22  5174.9 2456.17  5203.0 2458.21
  5291.9 2470.74  5298.0 2472.75  5319.3 2474.06  5324.1 2476.01  5327.0 2476.01
#Mann=3,-1,0
  4678.9    0.07       0  5011.1    0.07       0  5015.1    0.07       0
Bank Sta=5011.1,5015.1
Exp/Cntr=0.3,0.1

Type RM Length L Ch R = 1,7956,498,498,498
BEGIN DESCRIPTION:
Bitter Creek Trib6T4 15.0
END DESCRIPTION:
XS GIS Cut Line= 3
      1435205.03      6810387.99      1435138.12      6810421.42
      1435054.99      6810488.00
#Sta/Elev= 27
  4925.2 2431.05  4928.0 2431.05  4933.6 2429.24  4939.2 2428.99  4947.6 2427.05
  4956.0 2425.26  4961.6 2424.74  4969.9 2422.49  4978.3 2420.88  4983.9 2420.69
  4992.3 2417.98  4998.9 2414.64  5004.5 2414.36  5004.7 2413.86  5008.2 2413.86
  5008.5 2414.36  5020.9 2415.80  5028.9 2419.59  5035.3 2421.61  5042.4 2425.13
  5056.1 2427.82  5064.1 2429.12  5078.5 2430.22  5092.9 2430.75  5099.3 2431.33
  5103.3 2432.18  5106.5 2432.18
#Mann=3,-1,0
  4925.2    0.07       0  5004.5    0.07       0  5008.5    0.07       0
Bank Sta=5004.5,5008.5
Exp/Cntr=0.3,0.1

Type RM Length L Ch R = 1,7458,487,487,487
BEGIN DESCRIPTION:
Bitter Creek Trib6T4 14.0
END DESCRIPTION:
XS GIS Cut Line= 3
      1435005.00      6809787.98      1434991.79      6809974.62
      1434904.99      6810088.01
#Sta/Elev= 30
  4812.9 2436.55  4815.4 2436.55  4833.0 2431.77  4843.0 2428.51  4853.0 2424.27
  4863.0 2418.13  4868.8 2415.91  4885.9 2410.30  4913.2 2408.21  4923.2 2408.70
  4943.2 2407.24  4963.3 2407.93  4973.3 2407.60  4983.3 2406.88  4996.6 2404.01
  4997.0 2403.51  5001.4 2403.51  5001.8 2404.01  5015.0 2406.91  5042.1 2411.76
  5050.3 2411.98  5079.4 2414.23  5085.7 2415.02  5100.2 2417.88  5114.7 2419.00
  5121.0 2418.99  5129.2 2420.13  5135.5 2419.96  5140.2 2421.13  5142.8 2421.13
#Mann=5,-1,0
  4812.9    0.07       0  4868.8    0.16       0  4996.6    0.07       0
  5001.8    0.16       0  5140.2    0.07       0
Bank Sta=4996.6,5001.8
Exp/Cntr=0.3,0.1

Type RM Length L Ch R = 1,6971,465,465,465
BEGIN DESCRIPTION:
Bitter Creek Trib6T4 13.0
END DESCRIPTION:
XS GIS Cut Line= 3
      1434605.00      6809738.00      1434559.52      6809837.94
      1434404.98      6810088.04
#Sta/Elev= 30
  4890.2 2425.77  4899.0 2425.54  4904.5 2424.14  4922.0 2423.56  4956.1 2419.22
  4967.1 2418.68  4973.7 2416.53  4979.1 2416.29  4989.1 2406.69  4996.7 2397.56
  4996.8 2396.60  4997.2 2396.10  5002.0 2396.60  5017.9 2399.34  5023.8 2398.12
  5039.2 2399.61  5047.1 2401.26  5052.0 2401.14  5091.2 2398.97  5173.1 2397.56
  5185.8 2399.00  5191.7 2397.86  5207.1 2404.83  5212.9 2404.78  5222.5 2411.97
  5228.3 2414.29  5243.7 2422.23  5249.6 2422.48  5265.0 2425.65  5294.0 2429.26
#Mann=5,-1,0
  4890.2    0.07       0  4996.8    0.07       0  5002.0    0.07       0
  5052.0    0.16       0  5173.1    0.07       0
Bank Sta=4996.8,5002
Exp/Cntr=0.3,0.1

Type RM Length L Ch R = 1,6506,495,495,495
BEGIN DESCRIPTION:
Bitter Creek Trib6T4 12.0
END DESCRIPTION:
XS GIS Cut Line= 3
      1434405.04      6809587.97      1434174.93      6809808.18
      1434105.01      6809887.98
#Sta/Elev= 30
  4681.5 2426.35  4685.0 2426.35  4688.6 2425.29  4731.1 2419.92  4770.3 2412.25
  4794.6 2407.02  4830.1 2401.83  4872.6 2398.91  4886.8 2396.39  4900.9 2395.01
  4922.0 2394.66  4943.4 2393.06  4978.6 2393.28  4985.8 2392.43  4996.5 2389.60
  5003.2 2389.60  5004.3 2387.77  5004.7 2387.27  5009.2 2387.27  5009.6 2387.77
  5013.6 2387.83  5021.2 2390.52  5027.8 2392.05  5036.4 2397.35  5042.1 2400.17
  5056.3 2408.84  5070.5 2413.49  5084.8 2419.09  5102.8 2422.97  5106.1 2422.97
#Mann=5,-1,0
  4681.5    0.07       0  4770.3    0.16       0  5004.3    0.07       0
  5009.6    0.16       0  5036.4    0.07       0
Bank Sta=5004.3,5009.6
Exp/Cntr=0.3,0.1

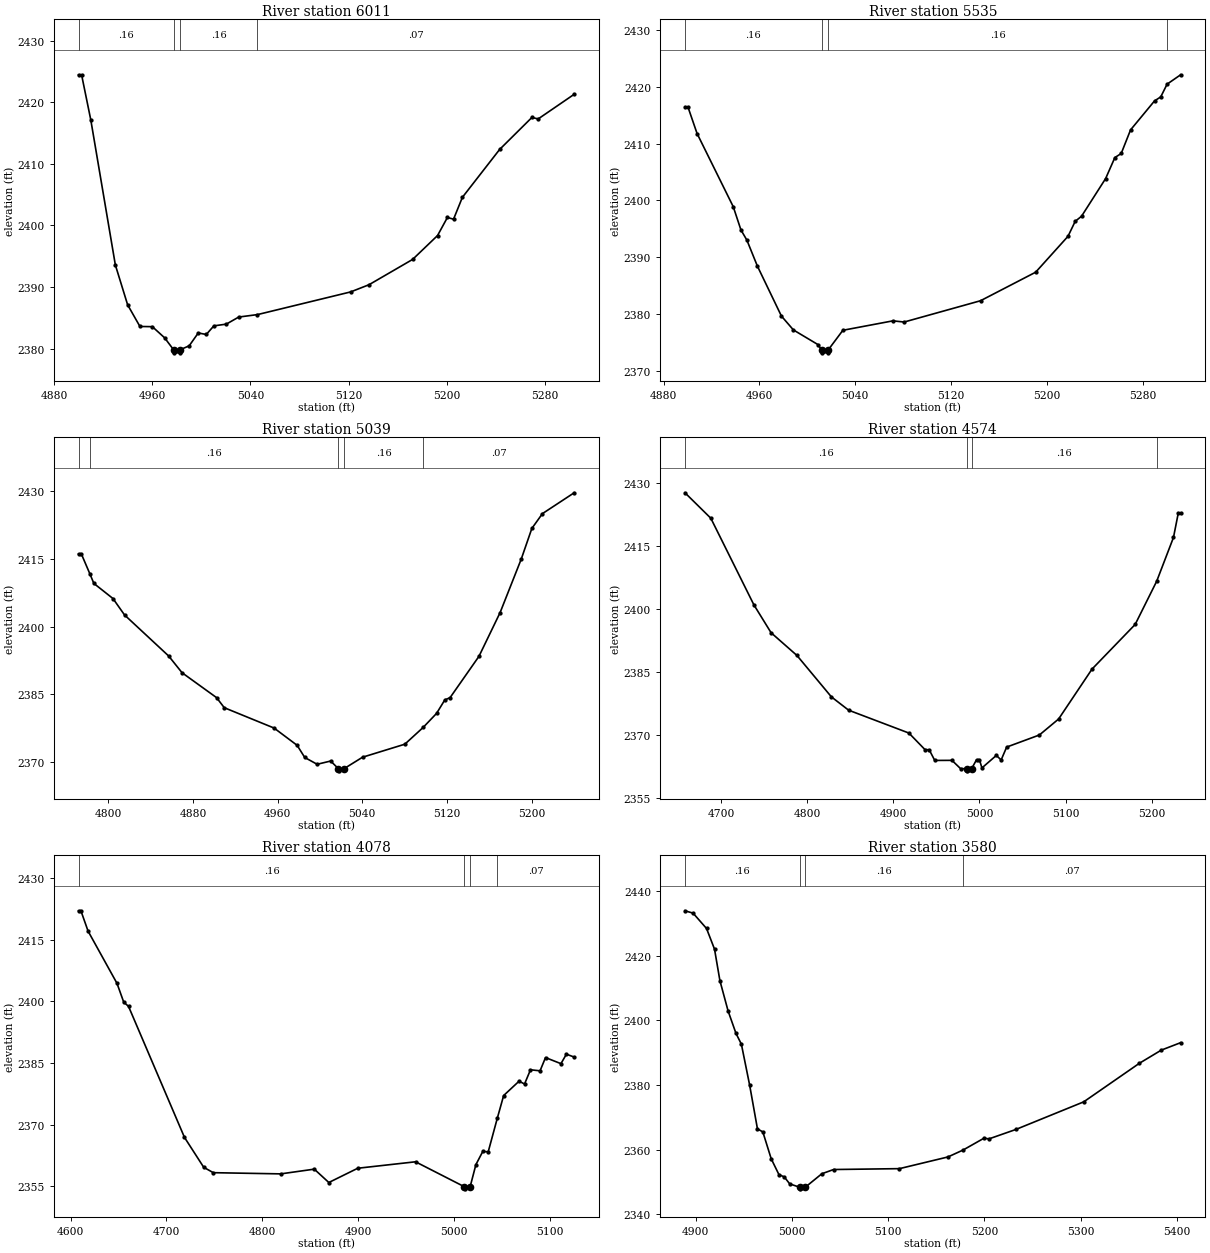
Type RM Length L Ch R = 1,6011,476,476,476
BEGIN DESCRIPTION:
Bitter Creek Trib6T4 11.0
END DESCRIPTION:
XS GIS Cut Line= 3
      1433805.00      6809438.01      1433809.59      6809537.90
      1433855.00      6809837.99
#Sta/Elev= 30
  4900.0 2424.47  4902.5 2424.47  4910.0 2417.14  4930.0 2393.58  4940.0 2387.11
  4950.0 2383.60  4960.1 2383.57  4970.1 2381.76  4977.4 2379.82  4977.8 2379.32
  4982.3 2379.32  4982.7 2379.82  4990.1 2380.46  4997.5 2382.55  5004.0 2382.30
  5010.2 2383.70  5020.3 2383.98  5030.4 2385.13  5045.7 2385.53  5121.5 2389.21
  5136.5 2390.38  5172.0 2394.49  5192.3 2398.37  5200.3 2401.30  5205.3 2401.02
  5212.5 2404.57  5242.8 2412.34  5269.1 2417.54  5274.2 2417.30  5303.5 2421.30
#Mann=4,-1,0
  4900.0    0.16       0  4977.4    0.07       0  4982.7    0.16       0
  5045.7    0.07       0
Bank Sta=4977.4,4982.7
Exp/Cntr=0.3,0.1

Type RM Length L Ch R = 1,5535,496,496,496
BEGIN DESCRIPTION:
Bitter Creek Trib6T4 10.0
END DESCRIPTION:
XS GIS Cut Line= 3
      1433355.00      6809537.96      1433365.62      6809639.51
      1433455.00      6809938.01
#Sta/Elev= 30
  4897.9 2416.37  4900.5 2416.37  4908.0 2411.77  4938.2 2398.89  4944.6 2394.81
  4949.6 2393.00  4958.3 2388.46  4978.4 2379.65  4988.4 2377.21  5008.9 2374.63
  5012.0 2373.68  5012.4 2373.18  5017.0 2373.18  5017.4 2373.68  5029.7 2377.15
  5071.5 2378.81  5080.8 2378.60  5144.6 2382.35  5190.6 2387.37  5217.6 2393.69
  5223.6 2396.32  5228.9 2397.22  5249.0 2403.85  5256.7 2407.54  5262.0 2408.26
  5269.8 2412.41  5289.8 2417.51  5295.0 2418.22  5300.3 2420.46  5311.6 2422.11
#Mann=4,-1,0
  4897.9    0.16       0  5012.0    0.07       0  5017.4    0.16       0
  5300.3    0.07       0
Bank Sta=5012,5017.4
Exp/Cntr=0.3,0.1

Type RM Length L Ch R = 1,5039,465,465,465
BEGIN DESCRIPTION:
Bitter Creek Trib6T4 9.0
END DESCRIPTION:
XS GIS Cut Line= 3
      1432855.02      6809538.04      1432944.95      6809747.88
      1432955.00      6809987.97
#Sta/Elev= 30
  4771.7 2416.07  4774.4 2416.07  4782.6 2411.59  4786.2 2409.56  4804.3 2406.21
  4815.2 2402.59  4856.9 2393.52  4869.6 2389.81  4902.2 2384.31  4909.5 2382.08
  4956.6 2377.58  4978.4 2373.76  4985.6 2371.07  4997.3 2369.57  5010.1 2370.29
  5017.3 2368.62  5017.8 2368.12  5022.9 2368.62  5040.2 2371.13  5080.2 2374.01
  5097.5 2377.71  5110.2 2380.82  5118.0 2383.80  5123.0 2384.31  5150.3 2393.44
  5170.3 2403.12  5190.3 2414.96  5200.3 2421.72  5210.3 2424.99  5240.3 2429.60
#Mann=5,-1,0
  4771.7    0.07       0  4782.6    0.16       0  5017.3    0.07       0
  5022.9    0.16       0  5097.5    0.07       0
Bank Sta=5017.3,5022.9
Exp/Cntr=0.3,0.1

Type RM Length L Ch R = 1,4574,496,496,496
BEGIN DESCRIPTION:
Bitter Creek Trib6T4 8.0
END DESCRIPTION:
XS GIS Cut Line= 3
      1432555.00      6809588.01      1432548.94      6809929.86
      1432655.00      6810137.99
#Sta/Elev= 30
  4658.1 2427.57  4688.1 2421.53  4738.1 2400.97  4758.1 2394.34  4788.1 2388.95
  4828.1 2379.12  4848.1 2375.96  4918.1 2370.53  4936.7 2366.61  4941.7 2366.55
  4948.1 2364.03  4968.1 2364.05  4978.1 2362.08  4985.3 2362.06  4985.8 2361.56
  4990.9 2362.06  4996.6 2364.19  5000.0 2364.19  5002.9 2362.25  5019.6 2365.22
  5025.2 2364.14  5031.6 2367.20  5069.6 2370.07  5091.9 2373.86  5130.7 2385.71
  5180.8 2396.31  5205.8 2406.57  5225.3 2416.97  5230.8 2422.68  5233.6 2422.68
#Mann=4,-1,0
  4658.1    0.16       0  4985.3    0.07       0  4990.9    0.16       0
  5205.8    0.07       0
Bank Sta=4985.3,4990.9
Exp/Cntr=0.3,0.1

Type RM Length L Ch R = 1,4078,498,498,498
BEGIN DESCRIPTION:
Bitter Creek Trib6T4 7.0
END DESCRIPTION:
XS GIS Cut Line= 3
      1432105.00      6809688.01      1432144.83      6810077.68
      1432205.02      6810188.03
#Sta/Elev= 30
  4608.3 2422.06  4610.8 2422.06  4618.3 2417.10  4648.5 2404.39  4655.5 2399.83
  4660.5 2398.81  4718.9 2366.94  4739.0 2359.66  4749.0 2358.35  4819.4 2358.06
  4854.4 2359.21  4869.6 2355.96  4899.8 2359.43  4960.1 2361.00  5011.2 2354.92
  5011.7 2354.42  5017.1 2354.92  5023.1 2360.30  5030.3 2363.51  5036.0 2363.44
  5045.4 2371.54  5052.1 2377.12  5068.2 2380.61  5073.9 2379.92  5080.1 2383.38
  5090.1 2383.13  5095.8 2386.35  5111.9 2384.87  5117.6 2387.18  5125.7 2386.47
#Mann=4,-1,0
  4608.3    0.16       0  5011.2    0.07       0  5017.1    0.16       0
  5045.4    0.07       0
Bank Sta=5011.2,5017.1
Exp/Cntr=0.3,0.1

Type RM Length L Ch R = 1,3580,497,497,497
BEGIN DESCRIPTION:
Bitter Creek Trib6T4 6.0
END DESCRIPTION:
XS GIS Cut Line= 3
      1431905.02      6809637.97      1431855.00      6809737.18
      1431905.00      6810137.97
#Sta/Elev= 30
  4888.9 2433.94  4897.3 2433.21  4911.3 2428.46  4919.6 2422.05  4925.2 2412.30
  4933.7 2402.92  4941.9 2395.98  4947.5 2392.65  4956.1 2379.95  4964.2 2366.43
  4969.8 2365.48  4978.5 2357.16  4986.5 2352.28  4992.1 2351.54  4997.7 2349.40
  5008.0 2348.36  5008.5 2347.86  5013.9 2348.36  5031.1 2352.53  5043.3 2353.84
  5111.7 2354.11  5162.1 2357.73  5177.9 2359.88  5199.6 2363.54  5204.7 2363.32
  5232.6 2366.23  5303.2 2374.79  5361.1 2386.74  5383.8 2390.80  5403.9 2393.11
#Mann=4,-1,0
  4888.9    0.16       0  5008.0    0.07       0  5013.9    0.16       0
  5177.9    0.07       0
Bank Sta=5008,5013.9
Exp/Cntr=0.3,0.1

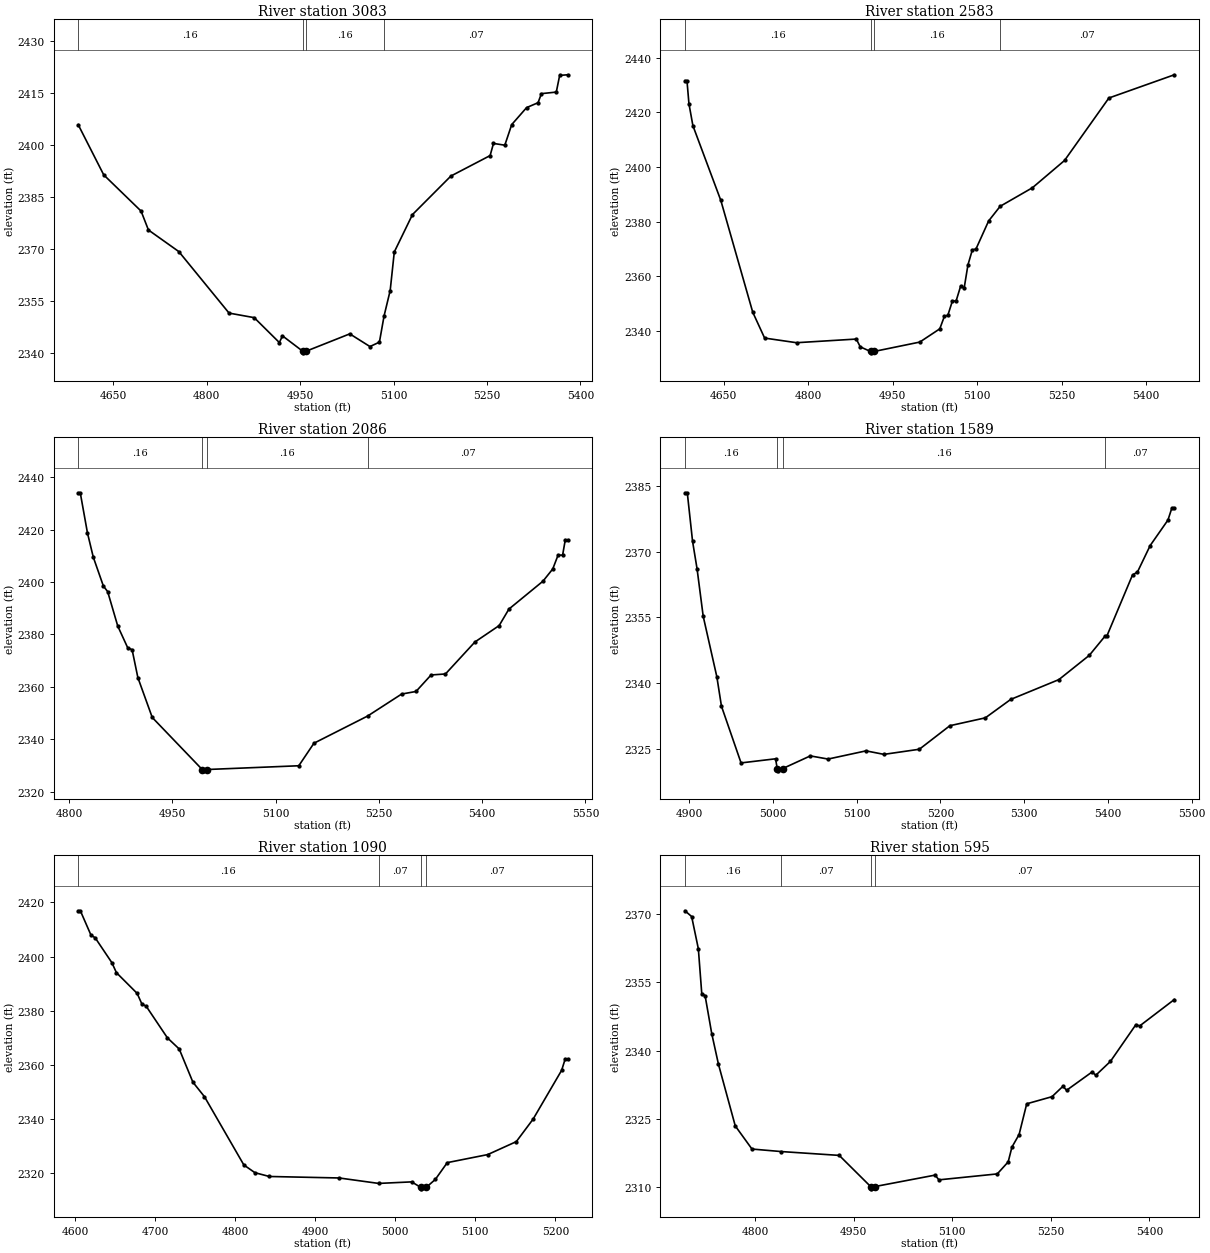
Type RM Length L Ch R = 1,3083,500,500,500
BEGIN DESCRIPTION:
Bitter Creek Trib6T4 5.0
END DESCRIPTION:
XS GIS Cut Line= 3
      1431555.01      6809637.96      1431499.25      6810040.61
      1431353.59      6810391.05
#Sta/Elev= 30
  4593.5 2405.82  4634.5 2391.38  4694.5 2380.95  4706.3 2375.51  4755.1 2369.30
  4835.8 2351.59  4876.2 2350.28  4916.6 2343.11  4921.6 2345.04  4953.9 2340.65
  4954.4 2340.15  4960.0 2340.65  5029.7 2345.61  5062.1 2341.96  5077.3 2343.23
  5084.8 2350.79  5094.6 2358.09  5101.2 2369.19  5130.4 2379.95  5192.1 2391.04
  5255.1 2396.93  5260.5 2400.43  5278.7 2399.92  5289.8 2405.85  5313.7 2410.74
  5332.1 2412.15  5337.5 2414.76  5361.4 2415.21  5366.8 2420.01  5379.5 2420.19
#Mann=4,-1,0
  4593.5    0.16       0  4953.9    0.07       0  4960.0    0.16       0
  5084.8    0.07       0
Bank Sta=4953.9,4960
Exp/Cntr=0.3,0.1

Type RM Length L Ch R = 1,2583,497,497,497
BEGIN DESCRIPTION:
Bitter Creek Trib6T4 4.0
END DESCRIPTION:
XS GIS Cut Line= 3
      1431505.03      6809537.97      1431210.74      6809835.67
      1430856.86      6810113.31
#Sta/Elev= 30
  4581.4 2431.59  4585.0 2431.59  4588.5 2423.17  4595.5 2415.14  4645.1 2387.72
  4701.7 2346.79  4722.8 2337.31  4779.4 2335.61  4885.5 2336.95  4892.5 2334.10
  4910.7 2332.40  4911.2 2331.90  4916.9 2332.40  4998.1 2335.84  5033.6 2340.69
  5041.7 2345.22  5048.0 2345.70  5056.1 2350.95  5062.5 2350.84  5070.6 2356.32
  5076.9 2355.64  5083.6 2364.11  5091.4 2369.63  5097.8 2369.92  5120.3 2380.22
  5140.8 2385.59  5198.0 2392.38  5255.0 2402.37  5333.7 2425.26  5449.8 2433.77
#Mann=4,-1,0
  4581.4    0.16       0  4910.7    0.07       0  4916.9    0.16       0
  5140.8    0.07       0
Bank Sta=4910.7,4916.9
Exp/Cntr=0.3,0.1

Type RM Length L Ch R = 1,2086,497,497,497
BEGIN DESCRIPTION:
Bitter Creek Trib6T4 3.0
END DESCRIPTION:
XS GIS Cut Line= 3
      1431154.97      6809288.04      1431044.52      6809438.93
      1430704.97      6809838.04
#Sta/Elev= 30
  4813.0 2434.10  4816.0 2434.10  4826.5 2418.71  4834.9 2409.54  4849.6 2398.49
  4855.8 2396.38  4870.5 2383.20  4885.1 2374.83  4891.3 2374.23  4899.7 2363.54
  4920.6 2348.32  4993.2 2328.45  4993.7 2327.95  4999.5 2328.45  5133.5 2329.89
  5155.5 2338.49  5233.5 2348.87  5282.9 2357.26  5303.8 2358.25  5325.7 2364.55
  5346.6 2364.93  5389.4 2377.14  5424.6 2383.40  5438.8 2389.70  5488.3 2400.36
  5502.5 2405.03  5510.2 2410.29  5516.8 2410.30  5520.7 2416.15  5524.0 2416.15
#Mann=4,-1,0
  4813.0    0.16       0  4993.2    0.07       0  4999.5    0.16       0
  5233.5    0.07       0
Bank Sta=4993.2,4999.5
Exp/Cntr=0.3,0.1

Type RM Length L Ch R = 1,1589,499,499,499
BEGIN DESCRIPTION:
Bitter Creek Trib6T4 2.0
END DESCRIPTION:
XS GIS Cut Line= 3
      1430705.02      6809187.96      1430663.50      6809284.40
      1430404.99      6809688.01
#Sta/Elev= 30
  4895.0 2383.41  4897.8 2383.41  4904.1 2372.33  4909.5 2366.02  4916.8 2355.22
  4933.1 2341.39  4938.6 2334.69  4962.0 2321.74  5003.2 2322.68  5005.2 2320.43
  5005.7 2319.93  5011.5 2320.43  5044.7 2323.34  5065.9 2322.62  5111.2 2324.49
  5132.6 2323.69  5174.9 2324.86  5211.3 2330.23  5253.7 2332.03  5284.0 2336.24
  5341.5 2340.76  5377.8 2346.30  5396.8 2350.73  5399.0 2350.81  5429.4 2364.65
  5435.3 2365.32  5450.5 2371.37  5471.7 2377.18  5476.3 2379.88  5479.3 2379.88
#Mann=4,-1,0
  4895.0    0.16       0  5005.2    0.07       0  5011.5    0.16       0
  5396.8    0.07       0
Bank Sta=5005.2,5011.5
Exp/Cntr=0.3,0.1

Type RM Length L Ch R = 1,1090,495,495,495
BEGIN DESCRIPTION:
Bitter Creek Trib6T4 1.0
END DESCRIPTION:
XS GIS Cut Line= 3
      1430655.05      6808987.98      1430278.25      6809111.41
      1430155.03      6809287.96
#Sta/Elev= 30
  4603.5 2416.91  4606.2 2416.91  4619.5 2407.91  4624.7 2406.95  4645.6 2397.76
  4651.3 2394.07  4677.2 2386.43  4683.2 2382.46  4688.4 2381.74  4715.0 2370.03
  4729.8 2365.91  4746.9 2353.67  4761.4 2348.29  4810.6 2323.12  4824.5 2320.26
  4842.4 2318.87  4929.8 2318.32  4979.1 2316.31  5020.4 2316.88  5032.0 2314.81
  5032.5 2314.31  5038.4 2314.81  5050.0 2317.79  5064.9 2323.98  5115.5 2326.95
  5151.2 2331.73  5172.2 2340.02  5207.9 2358.05  5212.3 2362.20  5215.3 2362.20
#Mann=4,-1,0
  4603.5    0.16       0  4979.1    0.07       0  5032.0    0.07       0
  5038.4    0.07       0
Bank Sta=5032,5038.4
Exp/Cntr=0.3,0.1

Type RM Length L Ch R = 1,595,519,519,519
BEGIN DESCRIPTION:
Bitter Creek Trib6T4 0.1
END DESCRIPTION:
XS GIS Cut Line= 3
      1430355.04      6808637.99      1430054.18      6808698.07
      1429854.98      6809088.04
#Sta/Elev= 30
  4693.2 2370.80  4703.4 2369.53  4713.6 2362.43  4718.8 2352.54  4723.9 2352.07
  4734.0 2343.71  4744.2 2336.98  4769.8 2323.38  4795.2 2318.29  4839.4 2317.74
  4928.0 2316.89  4975.8 2310.02  4976.3 2309.52  4982.2 2310.02  5074.0 2312.55
  5079.6 2311.50  5168.5 2312.81  5185.1 2315.46  5190.8 2318.72  5201.7 2321.49
  5213.3 2328.26  5251.8 2329.83  5268.4 2332.12  5274.0 2331.24  5312.8 2335.28
  5318.4 2334.55  5340.7 2337.61  5379.5 2345.72  5385.1 2345.41  5437.9 2351.24
#Mann=4,-1,0
  4693.2    0.16       0  4839.4    0.07       0  4975.8    0.07       0
  4982.2    0.07       0
Bank Sta=4975.8,4982.2
Exp/Cntr=0.3,0.1

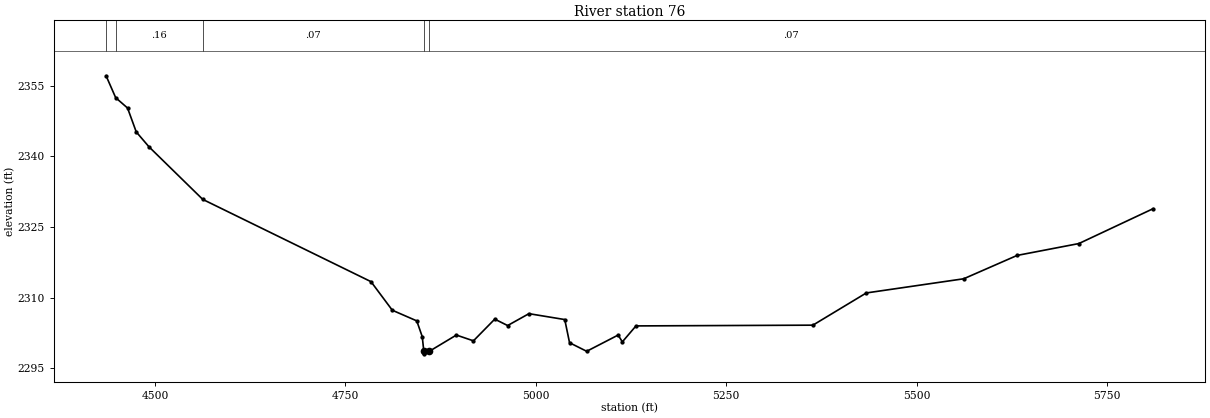
Type RM Length L Ch R = 1,76,0,0,0
BEGIN DESCRIPTION:
Bitter Creek Trib6T4 4308
END DESCRIPTION:
XS GIS Cut Line= 3
      1430430.51      6808507.91      1429924.82      6808257.49
      1429599.88      6808999.78
#Sta/Elev= 30
  4435.7 2357.09  4448.3 2352.44  4463.9 2350.24  4475.3 2345.17  4492.0 2342.01
  4562.6 2330.84  4783.5 2313.37  4811.5 2307.30  4843.6 2305.04  4850.8 2301.69
  4852.9 2298.54  4853.4 2298.04  4859.7 2298.54  4895.6 2302.03  4918.0 2300.80
  4946.0 2305.41  4962.9 2304.05  4990.9 2306.57  5037.9 2305.32  5044.2 2300.40
  5066.7 2298.58  5108.0 2302.03  5113.5 2300.58  5131.4 2303.97  5363.7 2304.13
  5433.8 2310.97  5561.7 2313.98  5631.8 2318.94  5712.9 2321.46  5810.3 2328.86
#Mann=5,-1,0
  4435.7    0.07       0  4448.3    0.16       0  4562.6    0.07       0
  4852.9    0.07       0  4859.7    0.07       0
Bank Sta=4852.9,4859.7
Exp/Cntr=0.3,0.1

Chan Stop Cuts=-1