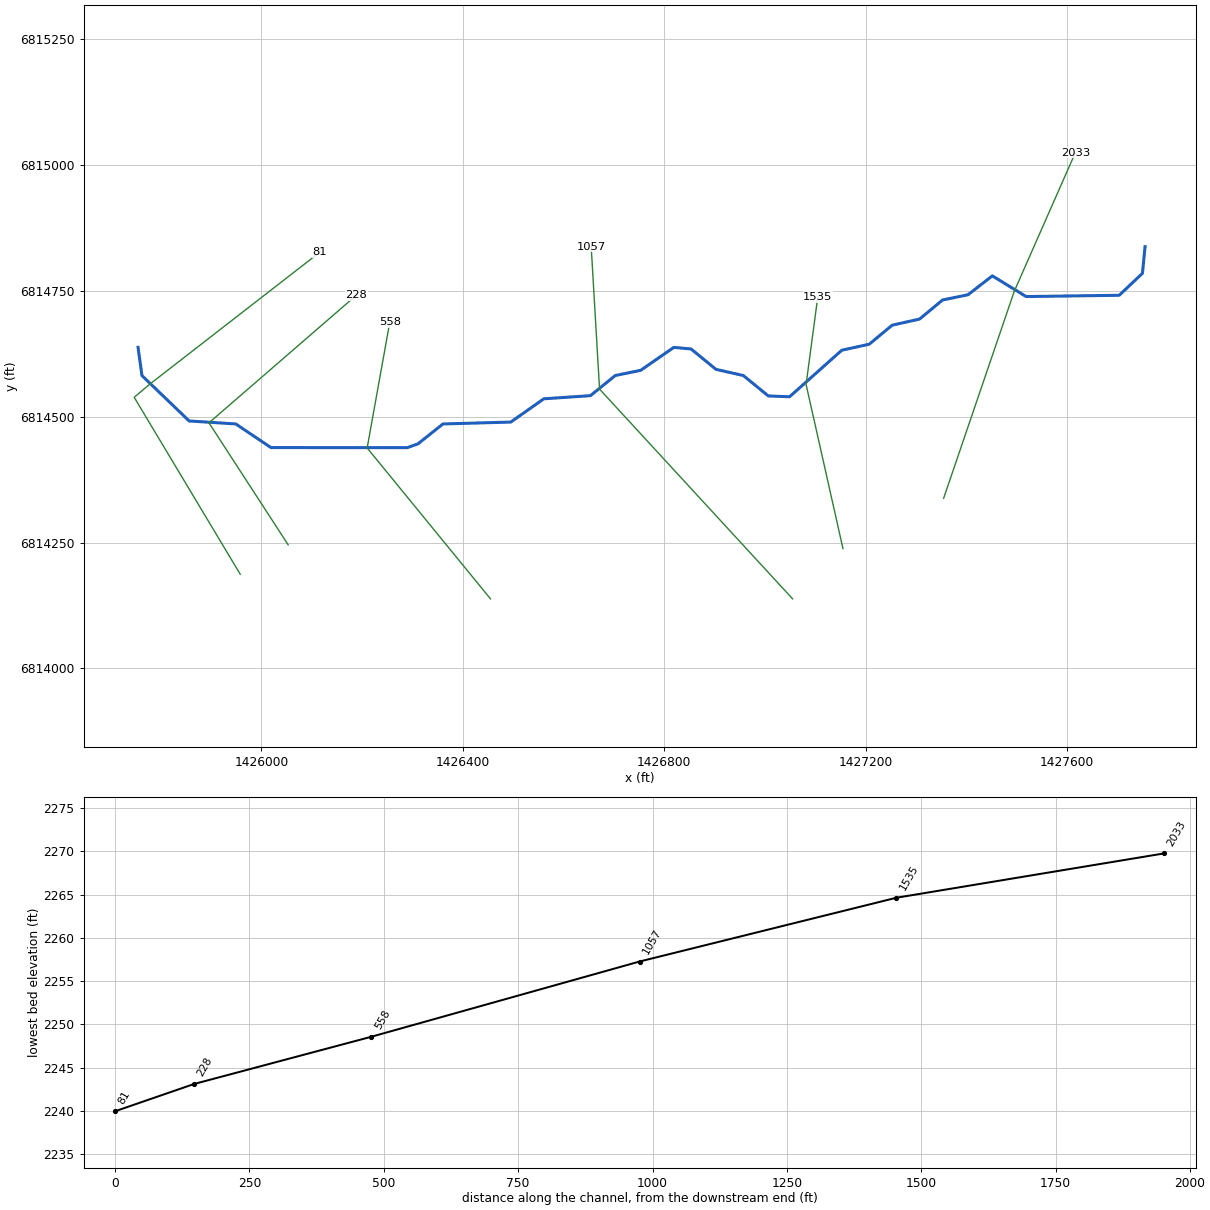
--- Bitter Creek Trib7.prj (project) ---

Proj Title=Bitter Creek Trib7 Base Level Engineering
Current Plan=p01
Default Exp/Contr=0.3,0.1
English Units
Geom File=g01
Flow File=f01
Plan File=p01
BEGIN DESCRIPTION:
Bitter Creek Trib7
END DESCRIPTION:

--- Bitter Creek Trib7.p01 (plan) ---

Plan Title=Multiple Run
Short Identifier=Multiple
Geom File=g01
Flow File=f01
Subcritical Flow
K Sum by GR= 0
Std Step Tol= 0.01
Critical Tol= 0.01
Num of Std Step Trials= 20
Max Error Tol= 0.3
Flow Tol Ratio= 0.001
Split Flow NTrial= 30
Split Flow Tol= 0.02
Split Flow Ratio= 0.02
Log Output Level= 0
Friction Slope Method= 1
Unsteady Friction Slope Method= 2
Unsteady Bridges Friction Slope Method= 1
Parabolic Critical Depth
Global Vel Dist=  1 , 1 , 1
Global Log Level= 0
CheckData=True
Encroach Param= -1, 0, 0, 0
BEGIN DESCRIPTION:
Multiple Run
END DESCRIPTION:

--- Bitter Creek Trib7.f01 (steady flow) ---

Flow Title=Multiple
Number of Profiles=7
Profile Names=10-year,25-year,50-year,1pct_min,100-year,1pct_plu,500-year
River Rch & RM= Bitter Creek Tri,Reach-1,2033
     490     723     927     592    1181    2356    1940
Boundary for River Rch & Prof#=Bitter Creek Tri,Reach-1,1
Up Type=0
Dn Type=3
Dn Slope=0.005
Boundary for River Rch & Prof#=Bitter Creek Tri,Reach-1,2
Up Type=0
Dn Type=3
Dn Slope=0.005
Boundary for River Rch & Prof#=Bitter Creek Tri,Reach-1,3
Up Type=0
Dn Type=3
Dn Slope=0.005
Boundary for River Rch & Prof#=Bitter Creek Tri,Reach-1,4
Up Type=0
Dn Type=3
Dn Slope=0.005
Boundary for River Rch & Prof#=Bitter Creek Tri,Reach-1,5
Up Type=0
Dn Type=3
Dn Slope=0.005
Boundary for River Rch & Prof#=Bitter Creek Tri,Reach-1,6
Up Type=0
Dn Type=3
Dn Slope=0.005
Boundary for River Rch & Prof#=Bitter Creek Tri,Reach-1,7
Up Type=0
Dn Type=3
Dn Slope=0.005

--- Bitter Creek Trib7.g01 (geometry) ---

Geom Title=Existing Conditions

River Reach=Bitter Creek Tri,Reach-1
Reach XY= 30
      1427755.00      6814838.00      1427749.87      6814785.05
      1427703.74      6814741.37      1427518.86      6814738.83
      1427451.68      6814779.96      1427403.36      6814742.43
      1427352.81      6814731.95      1427307.20      6814694.08
      1427252.80      6814681.92      1427207.19      6814644.10
      1427152.71      6814632.15      1427048.96      6814539.62
      1427006.74      6814541.31      1426957.20      6814581.85
      1426902.80      6814594.15      1426853.28      6814634.66
      1426819.10      6814637.78      1426753.28      6814592.22
      1426702.82      6814581.89      1426653.42      6814541.83
      1426560.98      6814535.64      1426495.33      6814489.39
      1426360.53      6814485.61      1426311.06      6814446.14
      1426289.78      6814438.52      1426018.92      6814438.68
      1425949.02      6814485.64      1425856.48      6814491.60
      1425762.75      6814581.76      1425755.00      6814638.00

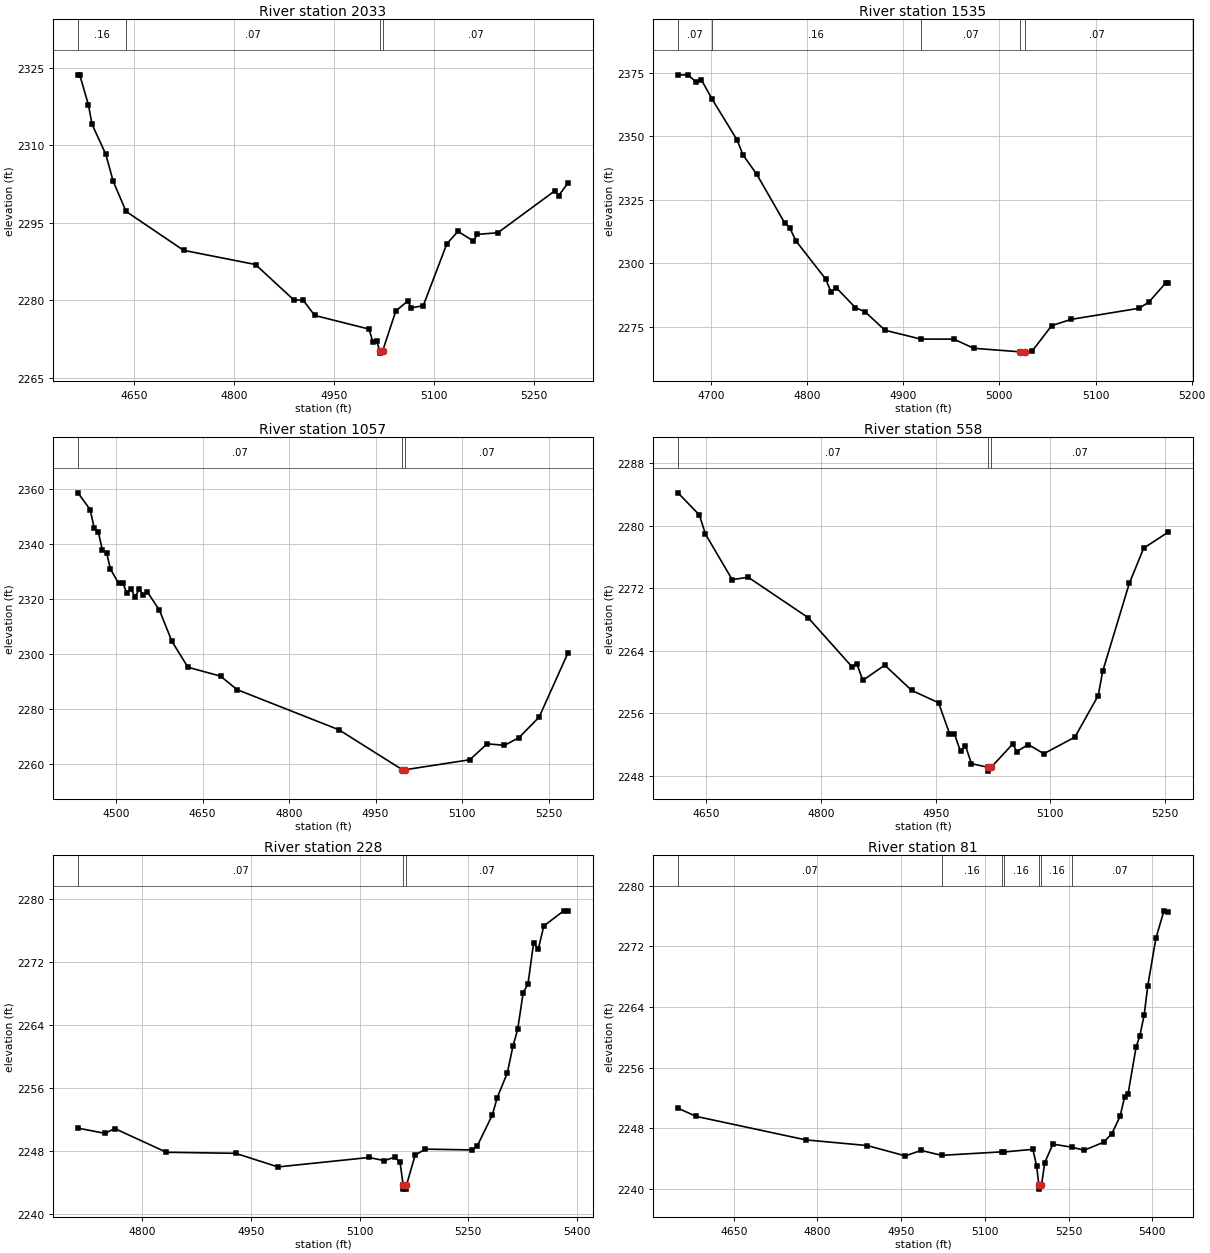
Type RM Length L Ch R = 1,2033,498,498,498
BEGIN DESCRIPTION:
Bitter Creek Trib7 3.0
END DESCRIPTION:
XS GIS Cut Line= 3
      1427354.99      6814337.96      1427495.21      6814749.21
      1427616.39      6815024.41
#Sta/Elev= 30
  4565.5 2323.65  4568.2 2323.65  4581.2 2317.86  4586.7 2314.07  4607.3 2308.27
  4618.4 2303.04  4637.7 2297.20  4724.0 2289.66  4831.9 2286.91  4889.3 2280.06
  4903.6 2279.97  4920.7 2277.05  5002.1 2274.41  5008.0 2271.92  5013.5 2272.08
  5018.3 2270.25  5018.6 2269.75  5022.8 2270.25  5042.4 2277.93  5060.1 2279.81
  5065.6 2278.53  5083.5 2278.92  5118.9 2290.92  5135.6 2293.33  5158.9 2291.45
  5164.4 2292.75  5195.4 2293.06  5281.1 2301.20  5286.5 2300.22  5300.7 2302.72
#Mann=4,-1,0
  4565.5    0.16       0  4637.7    0.07       0  5018.3    0.07       0
  5022.8    0.07       0
Bank Sta=5018.3,5022.8
Exp/Cntr=0.3,0.1

Type RM Length L Ch R = 1,1535,478,478,478
BEGIN DESCRIPTION:
Bitter Creek Trib7 2.0
END DESCRIPTION:
XS GIS Cut Line= 3
      1427155.00      6814238.02      1427081.80      6814564.10
      1427104.99      6814737.96
#Sta/Elev= 30
  4665.8 2374.12  4676.0 2374.19  4684.9 2371.31  4690.0 2372.33  4701.1 2364.75
  4727.3 2348.53  4733.3 2342.75  4747.8 2334.97  4776.7 2315.92  4781.8 2314.05
  4788.8 2308.63  4819.5 2293.75  4825.1 2288.52  4830.2 2290.44  4850.3 2282.55
  4860.5 2280.87  4881.0 2273.64  4918.3 2270.16  4952.8 2270.14  4973.2 2266.54
  5021.9 2265.13  5022.2 2264.63  5026.4 2265.13  5034.2 2265.49  5054.4 2275.46
  5074.6 2277.92  5145.2 2282.28  5155.3 2284.68  5172.9 2292.22  5175.4 2292.22
#Mann=5,-1,0
  4665.8    0.07       0  4701.1    0.16       0  4918.3    0.07       0
  5021.9    0.07       0  5026.4    0.07       0
Bank Sta=5021.9,5026.4
Exp/Cntr=0.3,0.1

Type RM Length L Ch R = 1,1057,499,499,499
BEGIN DESCRIPTION:
Bitter Creek Trib7 1.0
END DESCRIPTION:
XS GIS Cut Line= 3
      1427054.97      6814138.03      1426671.60      6814554.83
      1426655.00      6814838.05
#Sta/Elev= 30
  4433.7 2358.67  4454.9 2352.59  4461.7 2346.02  4469.1 2344.39  4475.9 2337.99
  4483.3 2336.91  4490.1 2330.89  4504.3 2325.66  4511.6 2325.74  4518.4 2322.23
  4525.8 2323.70  4532.6 2320.70  4540.0 2323.46  4546.8 2321.50  4554.2 2322.54
  4575.1 2315.90  4596.7 2304.54  4624.5 2295.12  4681.2 2291.86  4709.6 2286.97
  4886.5 2272.31  4996.5 2257.76  4996.8 2257.26  5001.1 2257.76  5113.4 2261.41
  5143.4 2267.22  5173.5 2266.66  5198.4 2269.42  5233.6 2276.95  5283.7 2300.39
#Mann=3,-1,0
  4433.7    0.07       0  4996.5    0.07       0  5001.1    0.07       0
Bank Sta=4996.5,5001.1
Exp/Cntr=0.3,0.1

Type RM Length L Ch R = 1,558,330,330,330
BEGIN DESCRIPTION:
Bitter Creek Trib7 0.1
END DESCRIPTION:
XS GIS Cut Line= 3
      1426454.98      6814138.03      1426210.04      6814437.91
      1426255.00      6814688.00
#Sta/Elev= 30
  4612.8 2284.24  4640.8 2281.40  4648.7 2278.96  4683.8 2273.11  4704.7 2273.42
  4782.9 2268.26  4840.4 2261.96  4846.8 2262.34  4854.7 2260.21  4883.4 2262.15
  4918.6 2258.92  4953.8 2257.33  4968.1 2253.38  4974.6 2253.33  4982.5 2251.09
  4989.0 2251.81  4996.8 2249.53  5018.1 2249.07  5018.4 2248.57  5022.7 2249.07
  5050.9 2252.06  5056.1 2251.07  5071.2 2251.98  5091.5 2250.80  5132.2 2252.93
  5162.7 2258.26  5168.5 2261.34  5203.3 2272.62  5222.2 2277.15  5254.1 2279.19
#Mann=3,-1,0
  4612.8    0.07       0  5018.1    0.07       0  5022.7    0.07       0
Bank Sta=5018.1,5022.7
Exp/Cntr=0.3,0.1

Type RM Length L Ch R = 1,228,147,147,147
BEGIN DESCRIPTION:
Bitter Creek Trib7 4309
END DESCRIPTION:
XS GIS Cut Line= 3
      1426053.11      6814245.49      1425895.84      6814487.83
      1426188.86      6814741.70
#Sta/Elev= 30
  4711.1 2250.86  4748.7 2250.19  4761.8 2250.81  4833.3 2247.79  4928.7 2247.66
  4987.3 2245.93  5113.1 2247.13  5133.9 2246.73  5148.2 2247.16  5155.8 2246.53
  5160.1 2243.61  5160.4 2243.11  5164.4 2243.11  5164.7 2243.61  5176.7 2247.45
  5190.9 2248.19  5254.6 2248.09  5262.2 2248.56  5283.1 2252.51  5290.0 2254.74
  5303.9 2257.87  5311.6 2261.24  5318.2 2263.41  5325.8 2268.08  5332.4 2269.15
  5340.1 2274.33  5346.7 2273.63  5354.3 2276.54  5381.8 2278.46  5387.7 2278.46
#Mann=3,-1,0
  4711.1    0.07       0  5160.1    0.07       0  5164.7    0.07       0
Bank Sta=5160.1,5164.7
Exp/Cntr=0.3,0.1

Type RM Length L Ch R = 1,81,0,0,0
BEGIN DESCRIPTION:
Bitter Creek Trib7 4310
END DESCRIPTION:
XS GIS Cut Line= 4
      1425957.88      6814187.01      1425747.37      6814538.58
      1425778.01      6814564.48      1426116.28      6814827.19
#Sta/Elev= 30
  4550.1 2250.64  4582.7 2249.56  4779.1 2246.46  4889.3 2245.71  4957.3 2244.35
  4985.9 2245.06  5022.8 2244.42  5130.0 2244.88  5133.8 2244.86  5186.1 2245.21
  5192.8 2243.00  5196.8 2240.46  5197.2 2239.96  5201.5 2240.46  5207.3 2243.43
  5221.8 2245.90  5256.4 2245.49  5277.9 2245.09  5313.2 2246.16  5327.7 2247.30
  5342.2 2249.55  5350.3 2252.07  5356.6 2252.52  5371.1 2258.75  5377.5 2260.11
  5385.6 2262.99  5391.9 2266.78  5406.4 2273.04  5420.9 2276.69  5428.3 2276.52
#Mann=7,-1,0
  4550.1    0.07       0  5022.8    0.16       0  5130.0    0.07       0
  5133.8    0.16       0  5196.8    0.07       0  5201.5    0.16       0
  5256.4    0.07       0
Bank Sta=5196.8,5201.5
Exp/Cntr=0.3,0.1

Chan Stop Cuts=-1