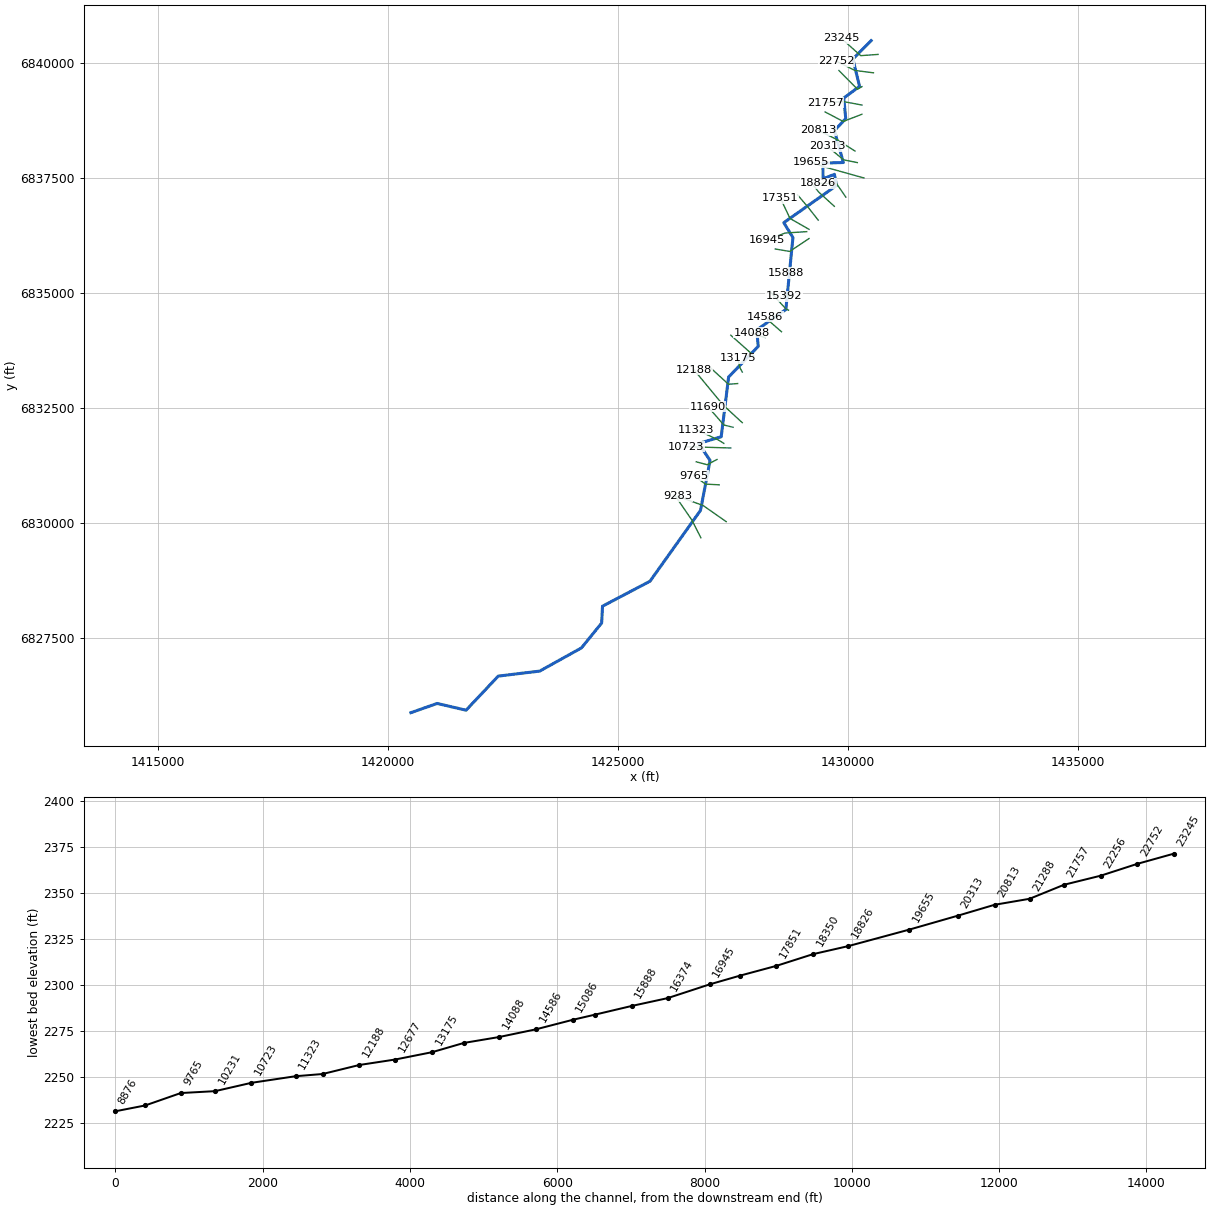
--- Bitter Creek Trib8.prj (project) ---

Proj Title=Bitter Creek Trib8 Base Level Engineering
Current Plan=p01
Default Exp/Contr=0.3,0.1
English Units
Geom File=g01
Flow File=f01
Plan File=p01
Y Axis Title=Elevation
X Axis Title(PF)=Main Channel Distance
X Axis Title(XS)=Station
BEGIN DESCRIPTION:
Bitter Creek Trib8
END DESCRIPTION:
DSS Export Rating Curves= 0
DSS Export Rating Curve Sorted= 0
DSS Export Volume Flow Curves= 0
DXF OffsetX= 0
DXF OffsetY= 0
DXF ScaleX= 1
DXF ScaleY= 10

--- Bitter Creek Trib8.p01 (plan) ---

Plan Title=Multiple Run
Short Identifier=Multiple
Geom File=g01
Flow File=f01
Subcritical Flow
K Sum by GR= 0
Std Step Tol= 0.01
Critical Tol= 0.01
Num of Std Step Trials= 20
Max Error Tol= 0.3
Flow Tol Ratio= 0.001
Split Flow NTrial= 30
Split Flow Tol= 0.02
Split Flow Ratio= 0.02
Log Output Level= 0
Friction Slope Method= 1
Unsteady Friction Slope Method= 2
Unsteady Bridges Friction Slope Method= 1
Parabolic Critical Depth
Global Vel Dist=  1 , 1 , 1
Global Log Level= 0
CheckData=True
Encroach Param= -1, 0, 0, 0
BEGIN DESCRIPTION:
Multiple Run
END DESCRIPTION:

--- Bitter Creek Trib8.f01 (steady flow) ---

Flow Title=Multiple
Number of Profiles=7
Profile Names=10-year,25-year,50-year,1pct_min,100-year,1pct_plu,500-year
River Rch & RM= Bitter Creek Tri,Reach-1,23245
     569     842    1082     690    1377    2748    2262
River Rch & RM= Bitter Creek Tri,Reach-1,14586
     915    1382    1801    1164    2322    4633    3913
River Rch & RM= Bitter Creek Tri,Reach-1,9283
    1125    1713    2242    1455    2903    5792    4932
River Rch & RM= Bitter Creek Tri,Reach-1,4827
    1815    2811    3722    2439    4867    9711    8437
Boundary for River Rch & Prof#=Bitter Creek Tri,Reach-1,1
Up Type=0
Dn Type=3
Dn Slope=0.005
Boundary for River Rch & Prof#=Bitter Creek Tri,Reach-1,2
Up Type=0
Dn Type=3
Dn Slope=0.005
Boundary for River Rch & Prof#=Bitter Creek Tri,Reach-1,3
Up Type=0
Dn Type=3
Dn Slope=0.005
Boundary for River Rch & Prof#=Bitter Creek Tri,Reach-1,4
Up Type=0
Dn Type=3
Dn Slope=0.005
Boundary for River Rch & Prof#=Bitter Creek Tri,Reach-1,5
Up Type=0
Dn Type=3
Dn Slope=0.005
Boundary for River Rch & Prof#=Bitter Creek Tri,Reach-1,6
Up Type=0
Dn Type=3
Dn Slope=0.005
Boundary for River Rch & Prof#=Bitter Creek Tri,Reach-1,7
Up Type=0
Dn Type=3
Dn Slope=0.005

--- Bitter Creek Trib8.g01 (geometry) ---

Geom Title=Existing Conditions
Program Version=4.10

River Reach=Bitter Creek Tri,Reach-1
Reach XY= 30
        1430505.        6840488.      1430108.51      6840086.75
      1430253.22      6839494.13      1429910.45      6839240.47
      1429952.94      6838793.85      1429707.05      6838532.14
      1429901.54      6837839.47      1429456.48      6837826.52
      1429460.46      6837484.99      1429707.55      6837583.06
      1429751.55      6837339.25      1428606.98      6836532.33
      1428805.71      6836208.15      1428651.61      6834646.41
      1428017.96      6834201.56      1428051.84      6833846.34
      1427408.06      6833179.72      1427246.87      6831881.92
      1426758.32      6831736.31      1427005.47      6831367.84
      1426796.95      6830281.91      1425699.56      6828743.25
      1424668.37      6828201.32       1424649.3      6827835.46
      1424211.19      6827295.81      1423303.75      6826791.51
      1422402.55      6826682.53      1421703.54      6825941.54
      1421075.12      6826088.54        1420505.        6825888.

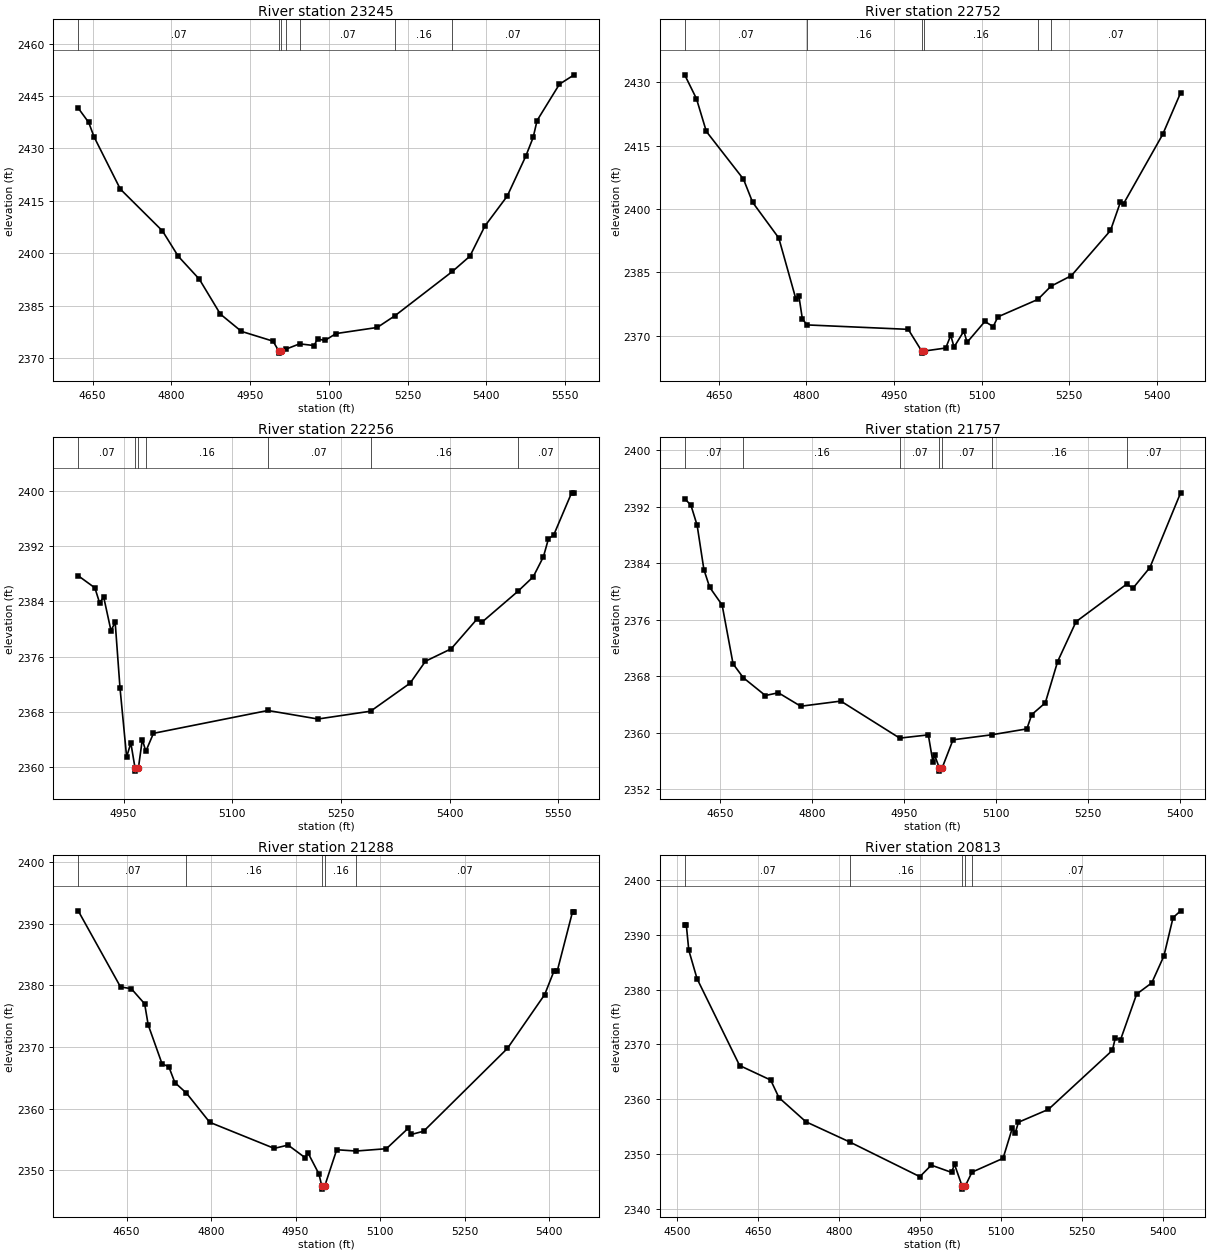
Type RM Length L Ch R = 1 ,23245   ,493,493,493
BEGIN DESCRIPTION:
Bitter Creek Trib8 43.0
END DESCRIPTION:
XS GIS Cut Line= 3
      1430654.99        6840188.      1430278.57      6840160.86
      1429855.03      6840537.97
#Sta/Elev= 30
  4622.6 2441.55  4642.6 2437.44  4652.7 2433.33  4702.8 2418.35    4783 2406.38
  4813.1 2399.11  4853.2 2392.56  4893.3 2382.55  4933.4  2377.6  4993.6  2374.8
    5005 2371.87  5005.4 2371.37  5009.7 2371.87  5018.5 2372.53  5044.3 2374.03
  5071.7 2373.54  5078.4 2375.41  5092.6 2375.01  5113.5 2376.97  5192.1 2378.72
  5225.9 2382.09  5335.3 2394.77  5368.6 2399.14    5397 2407.74  5439.6 2416.33
  5474.8 2427.72    5489 2433.13  5496.5 2437.99  5539.1  2448.4  5567.1 2451.08
#Mann= 7 ,-1 , 0
  4622.6     .07       0    5005     .07       0  5009.7     .07       0
  5018.5     .16       0  5044.3     .07       0  5225.9     .16       0
  5335.3     .07       0
Bank Sta=5005,5009.7
XS Rating Curve= 0 ,0
Exp/Cntr=0.3,0.1

Type RM Length L Ch R = 1 ,22752   ,496,496,496
BEGIN DESCRIPTION:
Bitter Creek Trib8 42.0
END DESCRIPTION:
XS GIS Cut Line= 3
      1430554.99        6839788.      1430149.57      6839840.43
      1429754.98      6840038.01
#Sta/Elev= 30
  4591.2 2431.78  4611.4 2426.13  4628.3 2418.38    4692 2407.07  4707.7 2401.58
  4752.5 2393.14  4781.9 2378.66    4787 2379.37  4792.9 2374.01  4800.9 2372.56
  4974.4 2371.51  4997.4 2366.38  4997.7 2365.88  5002.1 2366.38  5038.7 2367.09
  5047.3  2370.1  5052.9 2367.31  5069.7 2371.07  5075.3 2368.44  5105.8 2373.38
    5120 2372.15  5128.1 2374.47  5196.5 2378.59    5219 2381.72  5254.1 2384.23
  5321.1 2394.92  5337.9 2401.56  5343.5 2401.26  5410.5 2417.65  5441.3 2427.53
#Mann= 6 ,-1 , 0
  4591.2     .07       0  4800.9     .16       0  4997.4     .07       0
  5002.1     .16       0  5196.5     .16       0    5219     .07       0
Bank Sta=4997.4,5002.1
XS Rating Curve= 0 ,0
Exp/Cntr=0.3,0.1

Type RM Length L Ch R = 1 ,22256   ,499,499,499
BEGIN DESCRIPTION:
Bitter Creek Trib8 41.0
END DESCRIPTION:
XS GIS Cut Line= 3
      1430304.97      6839487.98      1430207.42      6839431.94
        1429805.        6839838.
#Sta/Elev= 30
  4887.5 2387.69  4910.5 2385.94  4916.9 2383.81  4922.7 2384.58  4932.7 2379.76
  4938.5 2380.97  4945.1 2371.54  4954.3  2361.5  4960.1 2363.54  4965.8 2359.96
  4966.1 2359.46  4970.6 2359.96  4975.9 2364.01  4980.8 2362.33  4991.3 2364.92
  5149.2 2368.22  5218.2 2366.99  5290.9 2368.12  5345.4 2372.17  5366.6 2375.34
    5402 2377.13  5437.3 2381.38  5444.4 2380.97  5494.3 2385.46  5515.2 2387.53
  5529.3 2390.43  5536.3 2393.05  5543.4 2393.55  5568.2 2399.67  5571.7 2399.67
#Mann= 7 ,-1 , 0
  4887.5     .07       0  4965.8     .07       0  4970.6     .07       0
  4980.8     .16       0  5149.2     .07       0  5290.9     .16       0
  5494.3     .07       0
Bank Sta=4965.8,4970.6
XS Rating Curve= 0 ,0
Exp/Cntr=0.3,0.1

Type RM Length L Ch R = 1 ,21757   ,469,469,469
BEGIN DESCRIPTION:
Bitter Creek Trib8 40.0
END DESCRIPTION:
XS GIS Cut Line= 3
      1430304.98        6839088.      1429904.76      6839163.08
      1429505.05        6839138.
#Sta/Elev= 30
  4592.8 2393.17    4603 2392.23  4613.1 2389.38  4624.1 2383.11  4633.5  2380.6
  4653.8 2378.08  4671.6 2369.74  4688.2 2367.78  4724.2 2365.25  4745.4 2365.64
  4781.8 2363.73  4847.1 2364.46    4943 2359.21  4989.6 2359.67  4997.1 2355.82
  4999.8 2356.81  5007.3 2355.03  5007.6 2354.53  5012.3 2355.03  5029.8 2358.97
  5092.6 2359.68  5150.1 2360.52    5158 2362.54  5180.1 2364.21  5200.2 2370.07
  5230.2 2375.72  5312.6 2381.04    5323 2380.48  5350.5  2383.4  5400.5 2393.99
#Mann= 7 ,-1 , 0
  4592.8     .07       0  4688.2     .16       0    4943     .07       0
  5007.3     .07       0  5012.3     .07       0  5092.6     .16       0
  5312.6     .07       0
Bank Sta=5007.3,5012.3
XS Rating Curve= 0 ,0
Exp/Cntr=0.3,0.1

Type RM Length L Ch R = 1 ,21288   ,475,475,475
BEGIN DESCRIPTION:
Bitter Creek Trib8 39.0
END DESCRIPTION:
XS GIS Cut Line= 3
      1430305.03      6838888.01      1429898.51      6838731.26
      1429505.01        6838938.
#Sta/Elev= 30
  4564.3 2392.12  4639.4 2379.75  4658.5 2379.47  4682.2 2377.01  4688.5 2373.59
  4713.1 2367.26  4725.1 2366.79  4735.8 2364.22  4756.4  2362.5  4797.7 2357.76
  4912.2 2353.52  4936.8 2354.06  4966.8 2352.02  4972.2 2352.77  4991.4 2349.39
  4996.7  2347.4  4997.1  2346.9  5001.8  2347.4  5023.1  2353.3  5057.5 2353.09
  5111.3 2353.47  5149.7 2356.77  5155.4 2355.78  5177.4 2356.31  5326.1 2369.77
  5392.2 2378.51  5408.6 2382.31  5414.3 2382.27  5441.7 2391.99  5444.5 2391.99
#Mann= 5 ,-1 , 0
  4564.3     .07       0  4756.4     .16       0  4996.7     .07       0
  5001.8     .16       0  5057.5     .07       0
Bank Sta=4996.7,5001.8
XS Rating Curve= 0 ,0
Exp/Cntr=0.3,0.1

Type RM Length L Ch R = 1 ,20813   ,500,500,500
BEGIN DESCRIPTION:
Bitter Creek Trib8 38.0
END DESCRIPTION:
XS GIS Cut Line= 3
        1430155.        6838088.      1429743.86      6838347.53
        1429355.        6838538.
#Sta/Elev= 30
  4513.8  2391.8  4516.8  2391.8  4521.4 2387.18  4536.7 2381.99  4615.6 2366.17
  4673.2 2363.52  4688.5 2360.32  4738.5 2355.92  4820.3 2352.21  4949.7 2345.92
  4970.9 2348.02  5008.4  2346.7  5013.9 2348.16  5028.2 2344.15  5028.6 2343.65
  5033.5 2344.15  5046.3 2346.74  5103.9 2349.26  5120.9 2354.72  5126.4 2353.82
  5132.3 2355.83    5188 2358.18  5306.5 2368.93    5312  2371.2  5321.6 2370.85
  5351.5 2379.18  5379.5 2381.22    5402 2386.12    5419 2393.11    5433 2394.35
#Mann= 5 ,-1 , 0
  4513.8     .07       0  4820.3     .16       0  5028.2     .07       0
  5033.5     .16       0  5046.3     .07       0
Bank Sta=5028.2,5033.5
XS Rating Curve= 0 ,0
Exp/Cntr=0.3,0.1

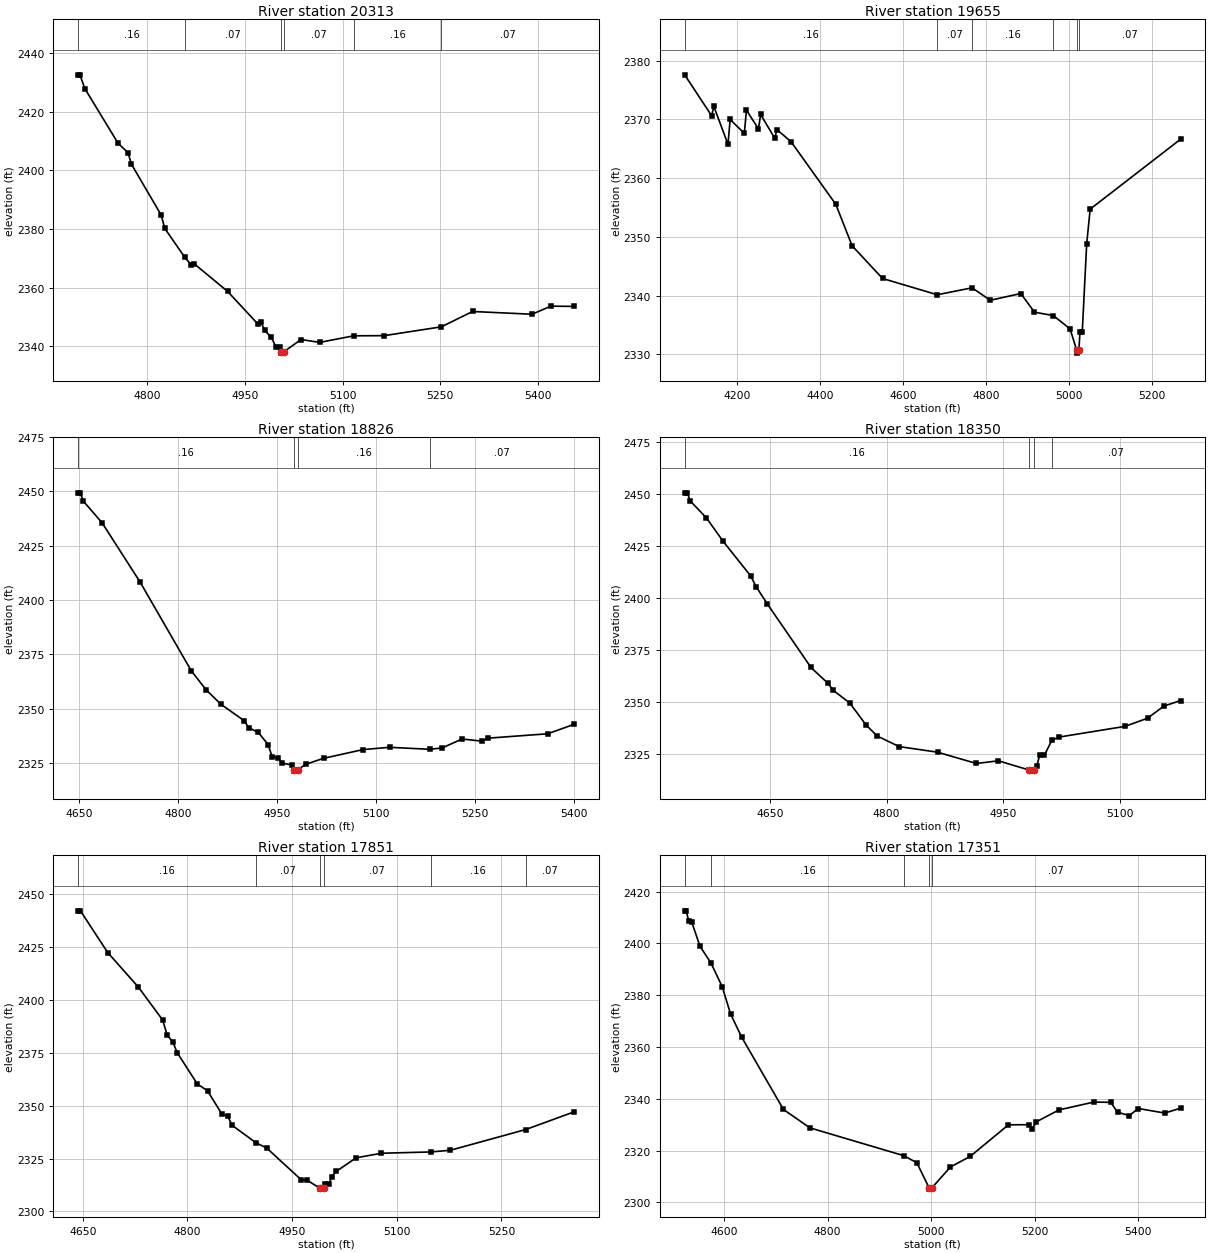
Type RM Length L Ch R = 1 ,20313   ,658,658,658
BEGIN DESCRIPTION:
Bitter Creek Trib8 37.0
END DESCRIPTION:
XS GIS Cut Line= 3
      1430205.03      6837837.99      1429905.79      6837898.04
      1429555.01      6838187.99
#Sta/Elev= 30
  4694.8 2432.56  4697.4 2432.56    4705 2427.84    4756 2409.22  4771.2 2405.99
  4776.4  2402.1  4822.1 2384.73  4827.4 2380.26  4857.9 2370.46  4867.9 2367.81
    4873 2368.09  4923.9 2358.74  4969.7 2347.76  4974.8 2348.46  4980.4  2345.5
  4990.6 2343.16  4997.9 2339.86  5003.8 2339.86    5005 2338.22  5005.4 2337.72
  5010.3 2338.22  5036.3 2342.35    5065 2341.38  5117.2 2343.62    5164 2343.68
  5251.5 2346.68  5299.4 2351.91  5390.6 2350.97  5419.3 2353.73  5455.1 2353.64
#Mann= 6 ,-1 , 0
  4694.8     .16       0  4857.9     .07       0    5005     .07       0
  5010.3     .07       0  5117.2     .16       0  5251.5     .07       0
Bank Sta=5005,5010.3
XS Rating Curve= 0 ,0
Exp/Cntr=0.3,0.1

Type RM Length L Ch R = 1 ,19655   ,829,829,829
BEGIN DESCRIPTION:
Bitter Creek Trib8 36.0
END DESCRIPTION:
XS GIS Cut Line= 3
      1430348.11      6837504.23      1429454.78      6837753.28
      1429203.95      6837851.57
#Sta/Elev= 30
  4072.6 2377.61  4137.7 2370.63  4142.9 2372.24  4177.1 2365.76  4182.3    2370
  4216.5 2367.63  4221.7 2371.58  4250.7  2368.4  4255.9 2370.85    4290  2366.8
  4295.2 2368.28  4329.4  2366.2  4437.2 2355.55  4476.6 2348.48  4550.1  2342.9
  4682.1 2340.13  4766.1 2341.31  4810.2 2339.19  4883.8 2340.34  4916.7 2337.16
  4962.2 2336.58  5002.6 2334.31  5018.6 2330.68    5019 2330.18  5023.9 2330.68
  5026.6 2333.86    5032 2333.74  5042.7 2348.77  5051.1 2354.72  5269.4 2366.64
#Mann= 6 ,-1 , 0
  4072.6     .16       0  4682.1     .07       0  4766.1     .16       0
  4962.2     .07       0  5018.6     .07       0  5023.9     .07       0
Bank Sta=5018.6,5023.9
XS Rating Curve= 0 ,0
Exp/Cntr=0.3,0.1

Type RM Length L Ch R = 1 ,18826   ,476,476,476
BEGIN DESCRIPTION:
Bitter Creek Trib8 35.0
END DESCRIPTION:
XS GIS Cut Line= 3
      1429955.01      6837087.98      1429755.52      6837377.75
      1429354.96        6837388.
#Sta/Elev= 30
  4648.2 2449.38  4651.3 2449.38  4655.7 2445.67  4684.6  2435.5  4742.2 2408.24
    4820  2367.3  4842.5 2358.59  4864.7 2352.01  4900.5 2344.34  4906.6 2341.27
  4921.5 2339.03  4936.4 2333.41  4942.4 2327.89  4951.3 2327.31  4957.3 2324.93
  4972.2 2324.07  4975.6 2321.72    4976 2321.22    4981 2321.72  4993.2 2324.35
  5020.5 2327.12  5080.6 2331.15  5120.6 2332.19    5182 2331.27  5200.4 2331.92
  5230.6 2336.01  5260.6 2335.04  5270.6 2336.41  5360.6 2338.42  5400.7 2342.79
#Mann= 4 ,-1 , 0
  4648.2     .16       0  4975.6     .07       0    4981     .16       0
    5182     .07       0
Bank Sta=4975.6,4981
XS Rating Curve= 0 ,0
Exp/Cntr=0.3,0.1

Type RM Length L Ch R = 1 ,18350   ,499,499,499
BEGIN DESCRIPTION:
Bitter Creek Trib8 34.0
END DESCRIPTION:
XS GIS Cut Line= 3
        1429705.        6836888.      1429365.61      6837198.06
      1429254.98      6837338.02
#Sta/Elev= 30
  4540.3  2450.7  4543.7  2450.7  4547.4 2446.81  4568.3 2438.63  4589.9 2427.32
  4625.1 2410.81  4632.5  2405.4  4646.7 2397.25  4702.8 2366.73  4724.4 2359.18
  4731.2  2355.8  4752.8  2349.6  4773.7 2339.06  4787.9 2333.79  4816.3 2328.67
  4865.6 2325.99  4915.6 2320.56  4943.9 2321.84  4983.8 2317.38  4984.2 2316.88
  4989.2 2317.38  4993.3 2319.25    4997 2324.49  5003.1 2324.49  5012.8  2331.8
  5022.1 2333.26    5107 2338.41  5135.9 2342.34  5156.7 2348.11  5178.4 2350.83
#Mann= 4 ,-1 , 0
  4540.3     .16       0  4983.8     .07       0  4989.2     .16       0
  5012.8     .07       0
Bank Sta=4983.8,4989.2
XS Rating Curve= 0 ,0
Exp/Cntr=0.3,0.1

Type RM Length L Ch R = 1 ,17851   ,500,500,500
BEGIN DESCRIPTION:
Bitter Creek Trib8 33.0
END DESCRIPTION:
XS GIS Cut Line= 3
      1429355.01      6836587.98      1429134.57      6836868.28
      1428904.99      6837138.01
#Sta/Elev= 30
  4643.4  2442.2  4646.6  2442.2  4685.9 2422.36  4729.3 2406.25  4764.5 2390.51
  4770.9 2383.38    4779 2380.19  4785.3 2375.04  4814.2 2360.24  4828.7 2357.05
  4849.5 2345.95  4857.6 2345.03  4863.9 2340.71  4897.9 2332.51  4913.6 2329.94
  4963.3 2314.85  4971.4 2314.74  4989.5 2311.01  4989.9 2310.51    4995 2311.01
  4996.6 2313.03  5003.1 2313.03  5006.6 2316.39  5013.2 2318.89  5041.7 2325.33
    5078 2327.49  5148.5  2328.1  5176.8  2328.9  5284.8 2338.71  5354.2 2347.08
#Mann= 6 ,-1 , 0
  4643.4     .16       0  4897.9     .07       0  4989.5     .07       0
    4995     .07       0  5148.5     .16       0  5284.8     .07       0
Bank Sta=4989.5,4995
XS Rating Curve= 0 ,0
Exp/Cntr=0.3,0.1

Type RM Length L Ch R = 1 ,17351   ,406,406,406
BEGIN DESCRIPTION:
Bitter Creek Trib8 32.0
END DESCRIPTION:
XS GIS Cut Line= 3
        1429155.        6836388.      1428741.76      6836624.44
      1428536.58      6837060.03
#Sta/Elev= 30
  4523.9 2412.55  4526.8 2412.55  4531.8 2408.57  4537.6 2408.18  4553.4 2398.89
  4574.5 2392.47  4596.6 2383.15  4612.4 2372.78    4634 2363.77  4714.6 2335.87
  4765.8 2328.77  4947.2 2318.03  4972.2  2315.3  4995.8 2305.63  4996.2 2305.13
  5001.3 2305.63  5037.1  2313.7  5075.2 2317.76    5149 2329.95  5189.1    2330
  5194.6 2328.33  5202.9 2331.12  5247.1 2335.74  5314.1 2338.74  5346.6 2338.62
  5359.7 2334.83  5382.4 2333.51  5399.7 2336.25  5450.8  2334.5  5481.5 2336.37
#Mann= 5 ,-1 , 0
  4523.9     .07       0  4574.5     .16       0  4947.2     .07       0
  4995.8     .07       0  5001.3     .07       0
Bank Sta=4995.8,5001.3
XS Rating Curve= 0 ,0
Exp/Cntr=0.3,0.1

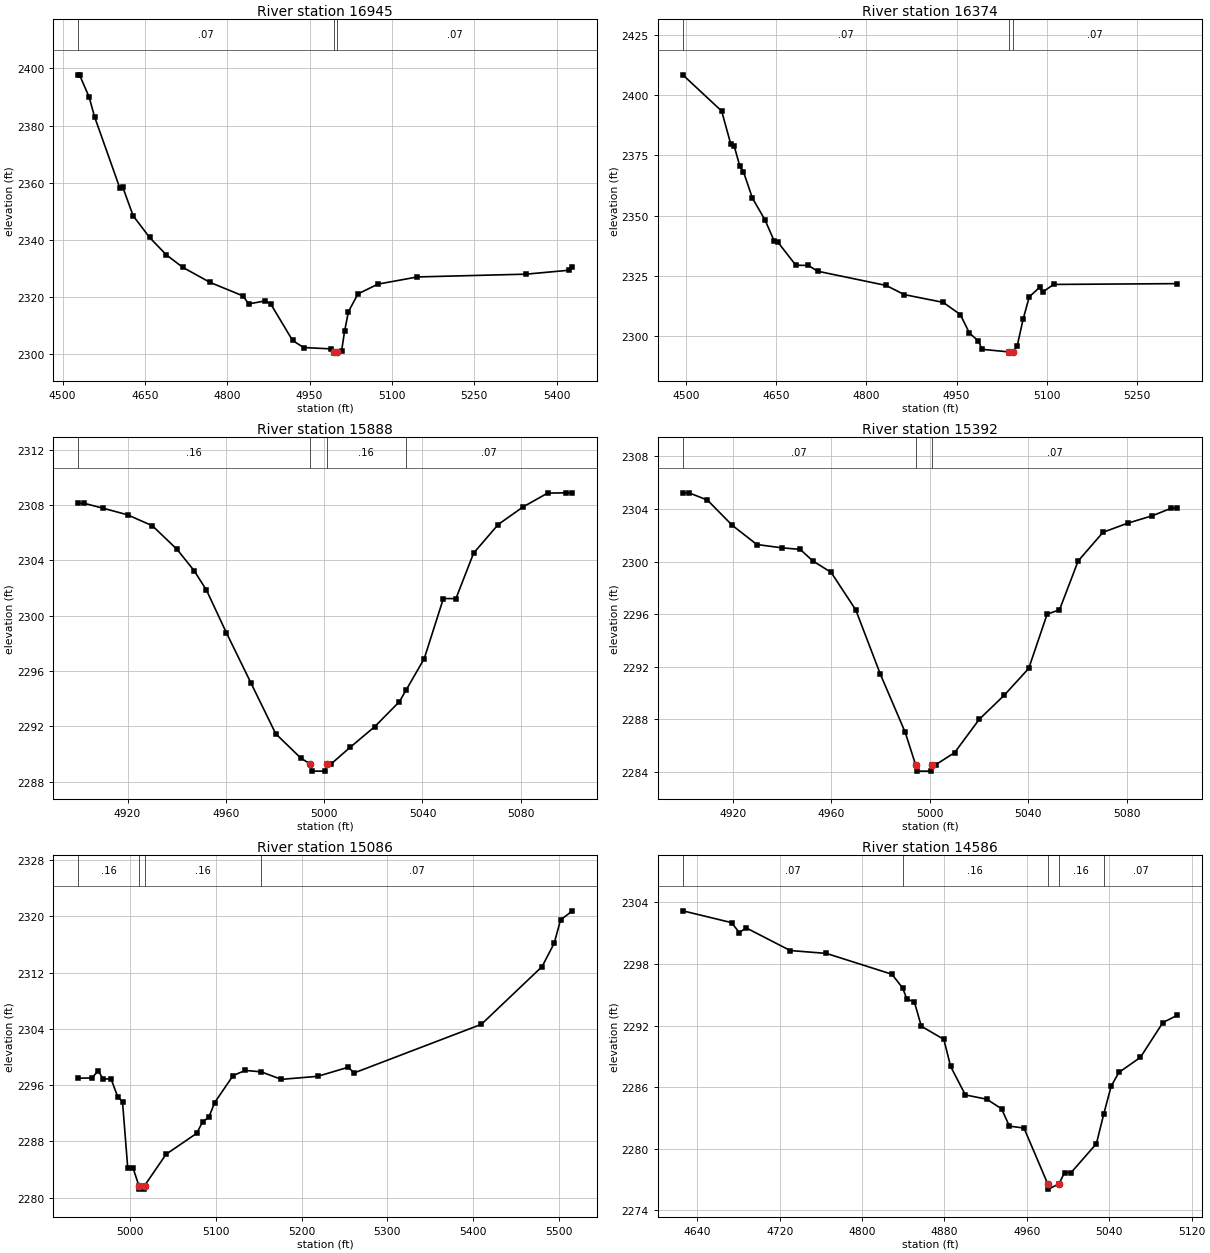
Type RM Length L Ch R = 1 ,16945   ,571,571,571
BEGIN DESCRIPTION:
Bitter Creek Trib8 31.0
END DESCRIPTION:
XS GIS Cut Line= 3
      1429104.96        6836338.      1428634.35      6836307.42
      1428234.95      6836150.83
#Sta/Elev= 30
  4528.4 2397.73  4530.9 2397.73  4548.4 2389.97  4558.4 2383.03  4604.5 2358.09
  4609.5 2358.59  4628.6 2348.47  4658.6 2340.89  4688.7 2334.88  4718.8 2330.47
  4768.9 2325.17    4829 2320.44    4839 2317.65  4869.1 2318.71  4879.1  2317.7
  4919.2 2304.88  4939.2 2302.42  4989.3 2301.94  4993.9 2300.96  4994.4 2300.46
  5000.4 2300.96  5008.4 2301.16  5013.8 2308.05  5020.8 2314.91  5038.2 2321.15
  5074.5 2324.57  5146.7 2327.09  5344.6 2328.06  5423.3 2329.44    5429 2330.48
#Mann= 3 ,-1 , 0
  4528.4     .07       0  4993.9     .07       0  5000.4     .07       0
Bank Sta=4993.9,5000.4
XS Rating Curve= 0 ,0
Exp/Cntr=0.3,0.1

Type RM Length L Ch R = 1 ,16374   ,486,486,486
BEGIN DESCRIPTION:
Bitter Creek Trib8 30.0
END DESCRIPTION:
XS GIS Cut Line= 3
      1429155.01      6836188.01      1428734.89      6835907.96
      1428422.87      6835961.05
#Sta/Elev= 30
  4495.1 2408.41  4559.7 2393.37  4574.7 2379.82  4580.7 2378.73  4589.8  2370.6
  4595.8 2368.29  4610.8 2357.28  4631.8  2348.2  4646.9 2339.54  4652.9 2339.09
  4682.9 2329.46  4703.9 2329.34    4719 2326.97  4833.1 2321.05  4863.2 2317.26
  4927.8 2314.04  4956.3 2308.98  4971.4 2301.34  4986.4 2297.99  4992.4 2294.57
  5037.2 2293.49  5037.7 2292.99  5043.8 2293.49  5050.6 2295.74  5060.8 2307.21
  5070.9 2316.35  5087.9 2320.23    5093 2318.32  5111.5 2321.48  5316.5 2321.81
#Mann= 3 ,-1 , 0
  4495.1     .07       0  5037.2     .07       0  5043.8     .07       0
Bank Sta=5037.2,5043.8
XS Rating Curve= 0 ,0
Exp/Cntr=0.3,0.1

Type RM Length L Ch R = 1 ,15888   ,496,496,496
BEGIN DESCRIPTION:
Bitter Creek Trib8 29.0
END DESCRIPTION:
XS GIS Cut Line= 3
      1428855.03        6835438.      1428755.45      6835427.81
      1428654.97        6835438.
#Sta/Elev= 30
  4899.9 2308.12  4902.4 2308.12    4910 2307.77    4920 2307.29  4930.1  2306.5
  4940.1  2304.8  4947.1 2303.25  4952.1 2301.85  4960.2 2298.77  4970.3  2295.1
  4980.3 2291.46  4990.4 2289.72  4994.4 2289.26  4994.9 2288.76  5000.5 2288.76
    5001 2289.26  5002.7 2289.26  5010.5 2290.47  5020.6 2291.98  5030.6 2293.78
  5033.3 2294.61  5040.7 2296.89  5048.5 2301.24  5053.6 2301.23  5060.8 2304.52
  5070.8 2306.59  5080.9 2307.86  5090.9 2308.86  5098.5 2308.88    5101 2308.88
#Mann= 4 ,-1 , 0
  4899.9     .16       0  4994.4     .07       0    5001     .16       0
  5033.3     .07       0
Bank Sta=4994.4,5001
XS Rating Curve= 0 ,0
Exp/Cntr=0.3,0.1

Type RM Length L Ch R = 1 ,15392   ,306,306,306
BEGIN DESCRIPTION:
Bitter Creek Trib8 28.0
END DESCRIPTION:
XS GIS Cut Line= 3
      1428804.95        6834938.      1428705.05      6834947.98
      1428605.05        6834938.
#Sta/Elev= 29
  4899.6 2305.23  4902.1 2305.23  4909.6 2304.68  4919.7 2302.76  4929.7  2301.3
  4939.8 2301.05  4947.3 2300.93  4952.4 2300.06  4959.9 2299.18  4969.9 2296.33
  4979.9 2291.44    4990 2287.02  4994.2 2284.57  4994.7 2284.07  5000.4 2284.07
  5000.9 2284.57  5002.5 2284.57  5010.1 2285.48  5020.1 2288.01  5030.2 2289.83
  5040.2 2291.88  5047.7 2296.01  5052.7 2296.33  5060.3 2300.05  5070.4 2302.23
  5080.4 2302.92  5090.5 2303.49    5098 2304.05  5100.5 2304.05
#Mann= 3 ,-1 , 0
  4899.6     .07       0  4994.2     .07       0  5000.9     .07       0
Bank Sta=4994.2,5000.9
XS Rating Curve= 0 ,0
Exp/Cntr=0.3,0.1

Type RM Length L Ch R = 1 ,15086   ,500,500,500
BEGIN DESCRIPTION:
Bitter Creek Trib8 27.0
END DESCRIPTION:
XS GIS Cut Line= 3
      1428709.56      6834632.01      1428654.73      6834658.28
      1428305.02      6835037.98
#Sta/Elev= 30
  4939.2 2296.99  4955.3 2297.03  4962.8 2298.06  4968.3 2296.85  4977.5 2296.93
  4985.4 2294.36    4991 2293.66  4997.1 2284.26  5003.2 2284.26  5010.1 2281.73
  5010.6 2281.23  5016.3 2281.23  5016.8 2281.73  5041.9 2286.19  5077.6 2289.16
  5084.4 2290.77  5091.8 2291.45  5098.6 2293.53  5120.1 2297.37  5134.3  2298.1
  5152.8  2297.9  5176.4 2296.83  5218.8 2297.26  5254.5 2298.55  5261.3 2297.74
  5409.9 2304.65  5480.8 2312.86    5495  2316.2  5502.3 2319.48  5516.2 2320.78
#Mann= 4 ,-1 , 0
  4939.2     .16       0  5010.1     .07       0  5016.8     .16       0
  5152.8     .07       0
Bank Sta=5010.1,5016.8
XS Rating Curve= 0 ,0
Exp/Cntr=0.3,0.1

Type RM Length L Ch R = 1 ,14586   ,498,498,498
BEGIN DESCRIPTION:
Bitter Creek Trib8 26.0
END DESCRIPTION:
XS GIS Cut Line= 3
      1428557.19      6834163.28       1428274.8      6834408.49
        1428205.        6834488.
#Sta/Elev= 30
    4626 2303.18  4673.3 2302.03  4680.9 2301.06  4687.5 2301.52  4730.3 2299.31
  4765.4 2299.03    4829    2297  4839.5 2295.65  4843.3 2294.62  4850.9 2294.27
  4857.5 2291.94  4879.4 2290.65    4886 2288.01  4900.3 2285.24  4921.1 2284.82
  4935.4 2283.89    4943  2282.2  4957.2 2282.01  4980.3 2276.56  4980.8 2276.06
  4991.1 2276.56  4996.6 2277.68    5003 2277.68  5027.5 2280.49  5034.6 2283.37
  5041.8 2286.09  5049.3 2287.43  5070.2  2288.9    5092 2292.29  5105.8 2292.99
#Mann= 5 ,-1 , 0
    4626     .07       0  4839.5     .16       0  4980.3     .07       0
  4991.1     .16       0  5034.6     .07       0
Bank Sta=4980.3,4991.1
XS Rating Curve= 0 ,0
Exp/Cntr=0.3,0.1

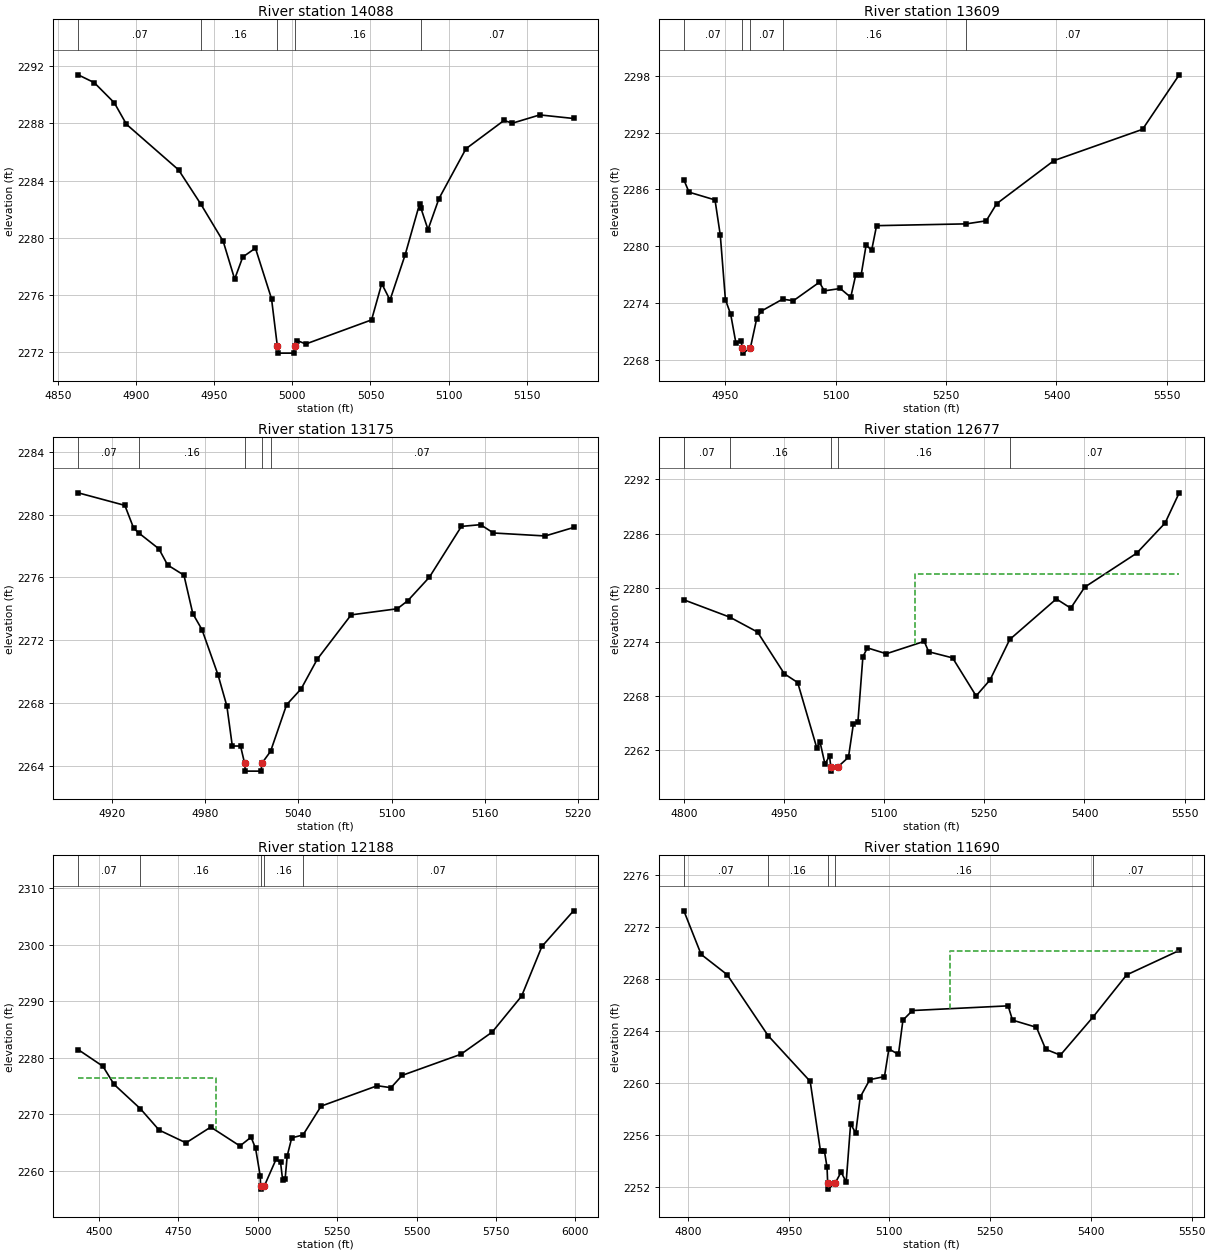
Type RM Length L Ch R = 1 ,14088   ,479,479,479
BEGIN DESCRIPTION:
Bitter Creek Trib8 25.0
END DESCRIPTION:
XS GIS Cut Line= 3
      1428204.96      6834038.01      1428072.11      6834071.45
      1427904.97      6834138.01
#Sta/Elev= 30
    4863 2291.41  4873.3 2290.86  4886.1 2289.45  4893.9 2287.94  4927.2 2284.75
  4941.5 2282.34  4955.8 2279.73  4963.1 2277.09  4968.3 2278.64  4976.4 2279.26
  4986.7 2275.71  4990.4  2272.4  4990.9  2271.9  5000.9  2271.9  5001.4  2272.4
  5003.2 2272.78  5008.6 2272.54  5050.7 2274.23  5057.2 2276.77  5062.5 2275.62
  5072.2  2278.8  5081.4 2282.36  5082.2 2282.09  5086.8 2280.56  5093.8 2282.73
  5111.1 2286.23  5135.4 2288.21  5140.8 2288.02  5158.3  2288.6  5179.9 2288.35
#Mann= 5 ,-1 , 0
    4863     .07       0  4941.5     .16       0  4990.4     .07       0
  5001.4     .16       0  5082.2     .07       0
Bank Sta=4990.4,5001.4
XS Rating Curve= 0 ,0
Exp/Cntr=0.3,0.1

Type RM Length L Ch R = 1 ,13609   ,434,434,434
BEGIN DESCRIPTION:
Bitter Creek Trib8 24.0
END DESCRIPTION:
XS GIS Cut Line= 3
      1427954.97      6833638.03      1427878.35      6833711.28
        1427455.        6834088.
#Sta/Elev= 30
    4894    2287    4901  2285.7  4936.3 2284.88  4943.5 2281.13  4950.4 2274.35
  4957.6 2272.79  4964.6 2269.79  4971.8 2269.98  4973.2 2269.19  4973.7 2268.69
  4984.2 2269.19  4992.9 2272.34  4998.9 2273.12    5028 2274.39  5042.8 2274.23
    5078 2276.18  5084.8 2275.27  5106.4 2275.52  5120.6 2274.59  5127.3 2276.92
  5134.8 2276.97  5141.5 2280.11    5149 2279.56  5155.7 2282.16  5277.4 2282.35
  5304.6 2282.67  5318.8 2284.48  5396.5 2289.03  5516.9 2292.34  5566.7  2298.1
#Mann= 5 ,-1 , 0
    4894     .07       0  4973.2     .07       0  4984.2     .07       0
    5028     .16       0  5277.4     .07       0
Bank Sta=4973.2,4984.2
XS Rating Curve= 0 ,0
Exp/Cntr=0.3,0.1

Type RM Length L Ch R = 1 ,13175   ,498,498,498
BEGIN DESCRIPTION:
Bitter Creek Trib8 23.0
END DESCRIPTION:
XS GIS Cut Line= 3
        1427705.        6833288.      1427656.72      6833377.29
      1427604.99      6833588.03
#Sta/Elev= 30
  4898.5 2281.39  4928.5 2280.59  4934.2 2279.13  4937.6 2278.82  4950.4 2277.82
    4956 2276.79  4966.5 2276.14  4972.2 2273.69  4978.1 2272.67  4988.4 2269.79
  4994.1  2267.8  4997.6 2265.25  5002.9 2265.25  5005.5 2264.15    5006 2263.65
  5016.1 2263.65  5016.6 2264.15  5022.2 2264.91  5032.5 2267.88  5041.9  2268.9
  5052.2 2270.78    5074 2273.61  5103.7    2274  5110.5 2274.52  5124.3 2276.01
  5144.9 2279.25  5157.2 2279.36  5165.5 2278.83  5198.8 2278.64    5217 2279.18
#Mann= 5 ,-1 , 0
  4898.5     .07       0  4937.6     .16       0  5005.5     .07       0
  5016.6     .16       0  5022.2     .07       0
Bank Sta=5005.5,5016.6
XS Rating Curve= 0 ,0
Exp/Cntr=0.3,0.1

Type RM Length L Ch R = 1 ,12677   ,489,489,489
BEGIN DESCRIPTION:
Bitter Creek Trib8 22.0
END DESCRIPTION:
XS GIS Cut Line= 3
      1427605.05        6833038.      1427405.42      6833022.83
      1427005.02      6833387.98
#Sta/Elev= 30
  4799.8 2278.66  4868.7 2276.74  4910.2 2275.09  4950.3 2270.47  4970.3  2269.5
  4998.9 2262.27  5003.8 2262.91  5011.2 2260.47    5018 2261.38  5019.9 2260.19
  5020.4 2259.69    5031 2260.19  5046.4 2261.23  5053.8 2264.94  5060.5  2265.1
    5068 2272.35  5074.7 2273.34  5103.1 2272.69  5159.9 2274.06  5166.6 2272.91
  5202.4 2272.23  5237.6 2268.02  5258.5 2269.79    5288 2274.27  5357.8 2278.76
  5379.4 2277.74  5400.4 2280.07  5478.1 2283.82  5520.7 2287.16  5541.9 2290.51
#Mann= 5 ,-1 , 0
  4799.8     .07       0  4868.7     .16       0  5019.9     .07       0
    5031     .16       0    5288     .07       0
#XS Ineff= 2 , 0
                          5146.8          2281.5
Permanent Ineff=
       F       F
Bank Sta=5019.9,5031
XS Rating Curve= 0 ,0
Exp/Cntr=0.3,0.1

Type RM Length L Ch R = 1 ,12188   ,498,498,498
BEGIN DESCRIPTION:
Bitter Creek Trib8 21.0
END DESCRIPTION:
XS GIS Cut Line= 3
        1427705.        6832188.       1427288.5      6832571.26
        1426655.        6833338.
#Sta/Elev= 30
    4434 2281.44    4512 2278.48  4547.1 2275.27  4629.8 2270.97  4688.9 2267.18
  4773.7 2264.91  4851.7 2267.71  4943.6 2264.36  4978.7 2265.92  4992.9 2263.93
  5007.8 2258.97  5008.5 2257.21    5009 2256.71    5020 2257.21  5057.3 2261.98
  5071.6 2261.43  5078.1 2258.35    5086 2258.53  5092.5 2262.59  5106.8  2265.8
  5142.3 2266.31  5199.3 2271.42  5376.4 2275.04  5419.5 2274.69  5454.6 2276.87
  5639.6 2280.61  5738.6 2284.56  5831.1 2290.93  5894.9 2299.72  5994.6 2306.04
#Mann= 5 ,-1 , 0
    4434     .07       0  4629.8     .16       0  5008.5     .07       0
    5020     .16       0  5142.3     .07       0
#XS Ineff= 2 , 0
         4867.82 2276.42
Permanent Ineff=
       F       F
Bank Sta=5008.5,5020
XS Rating Curve= 0 ,0
Exp/Cntr=0.3,0.1

Type RM Length L Ch R = 1 ,11690   ,367,367,367
BEGIN DESCRIPTION:
Bitter Creek Trib8 20.0
END DESCRIPTION:
XS GIS Cut Line= 3
      1427504.96      6832088.01      1427305.02        6832138.
      1426955.01      6832537.99
#Sta/Elev= 30
  4793.9 2273.23  4819.6 2269.88  4858.3 2268.32  4919.3 2263.63    4982 2260.11
  4997.4 2254.72  5003.3 2254.72  5007.1  2253.5    5008 2252.32  5008.5 2251.82
  5019.6 2252.32    5028 2253.13  5035.6 2252.37  5042.2 2256.85  5049.8 2256.13
  5056.5  2258.9  5070.7 2260.24  5092.6 2260.48  5099.2 2262.61  5113.4 2262.18
  5120.1 2264.82  5134.3 2265.56  5276.7 2265.92  5283.3 2264.82  5318.9 2264.27
  5332.7 2262.58  5354.5 2262.13  5403.5 2265.08  5453.2  2268.3  5531.5 2270.18
#Mann= 5 ,-1 , 0
  4793.9     .07       0  4919.3     .16       0    5008     .07       0
  5019.6     .16       0  5403.5     .07       0
#XS Ineff= 2 , 0
                         5190.66         2270.11
Permanent Ineff=
       F       F
Bank Sta=5008,5019.6
XS Rating Curve= 0 ,0
Exp/Cntr=0.3,0.1

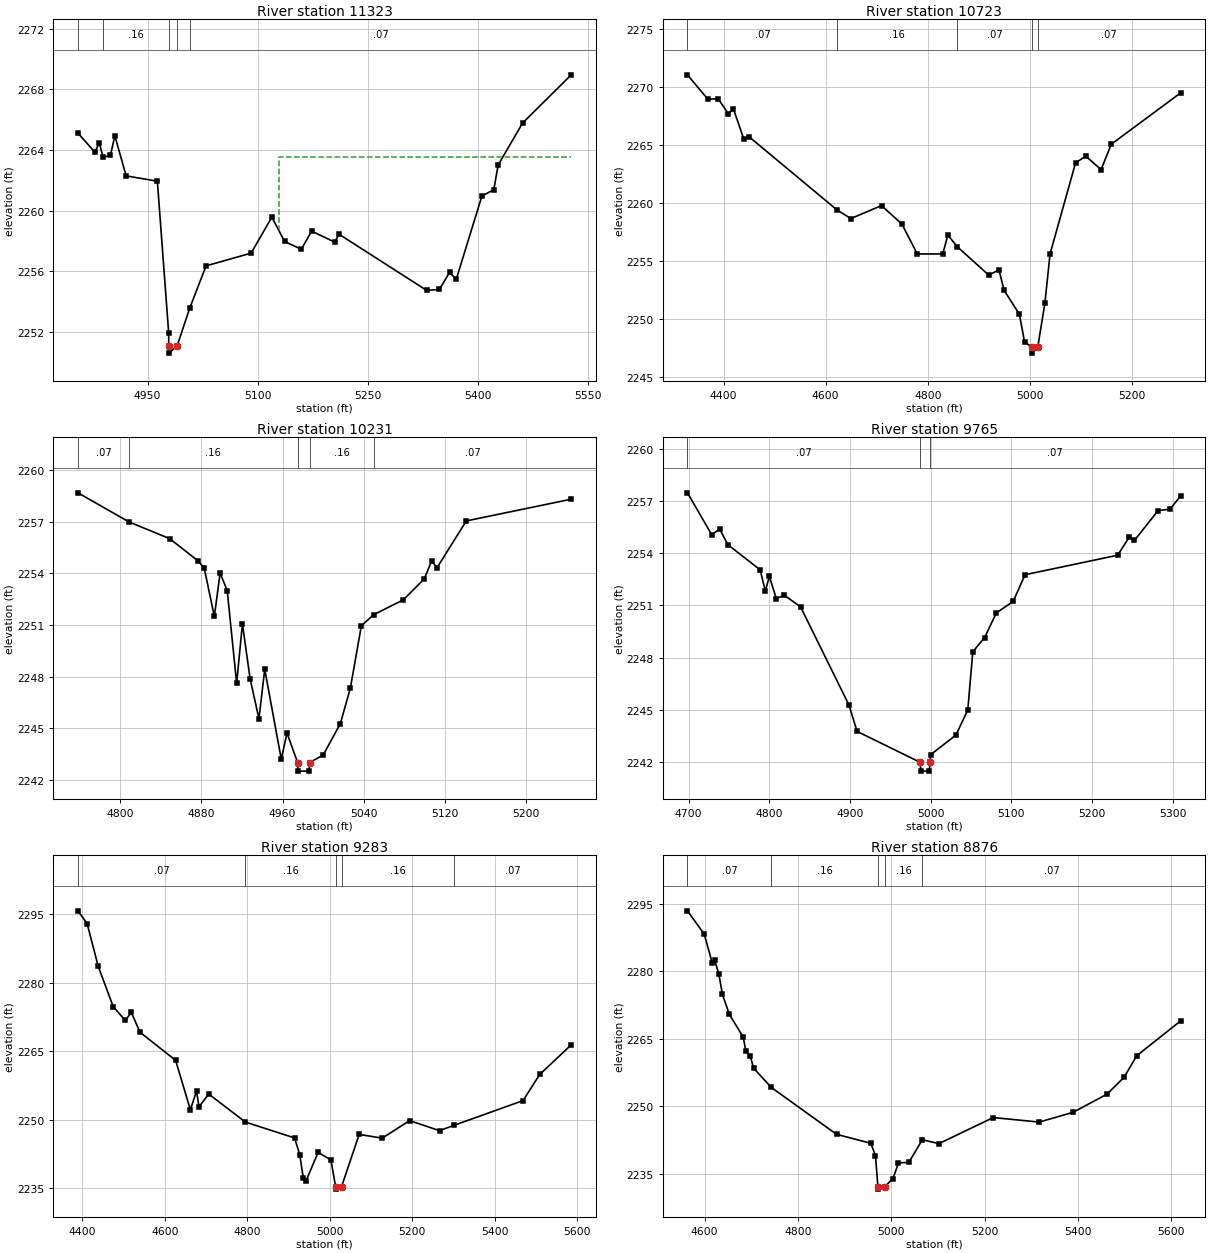
Type RM Length L Ch R = 1 ,11323   ,600,600,600
BEGIN DESCRIPTION:
Bitter Creek Trib8 19.0
END DESCRIPTION:
XS GIS Cut Line= 3
      1427304.99      6831738.01      1427181.93      6831814.13
      1426704.96      6832038.02
#Sta/Elev= 30
  4855.3 2265.12  4878.4 2263.86  4884.2 2264.49  4889.6 2263.52  4899.6 2263.66
  4905.5 2264.95  4920.9  2262.3  4963.4 2261.95  4978.8 2251.96  4978.9 2251.12
  4979.4 2250.62  4990.5 2251.12  5007.6  2253.6  5029.7 2256.37    5091 2257.21
  5119.3 2259.58  5136.6 2257.98  5159.4 2257.46  5173.4 2258.66  5205.1 2257.93
  5210.6 2258.46  5330.2 2254.75  5347.5 2254.82  5361.2 2255.94  5370.3 2255.48
  5405.3 2260.98  5421.4 2261.38  5427.4 2263.02  5460.6 2265.78  5526.9 2268.96
#Mann= 5 ,-1 , 0
  4855.3     .07       0  4889.6     .16       0  4978.9     .07       0
  4990.5     .16       0  5007.6     .07       0
#XS Ineff= 2 , 0
                         5128.93         2263.54
Permanent Ineff=
       F       F
Bank Sta=4978.9,4990.5
XS Rating Curve= 0 ,0
Exp/Cntr=0.3,0.1

Type RM Length L Ch R = 1 ,10723   ,492,492,492
BEGIN DESCRIPTION:
Bitter Creek Trib8 18.0
END DESCRIPTION:
XS GIS Cut Line= 3
      1427455.02        6831638.      1426784.61      6831657.93
      1426488.95       6831662.7
#Sta/Elev= 30
  4329.3 2271.08  4369.3 2268.97  4389.3 2269.02  4409.4 2267.72  4419.4 2268.13
  4439.4 2265.57  4449.4 2265.75  4622.9 2259.38  4649.5 2258.66  4709.5 2259.78
  4749.5 2258.18  4779.5  2255.6  4829.4  2255.6  4839.5 2257.23  4857.8 2256.23
  4919.6 2253.77  4939.6 2254.23  4949.6 2252.46  4979.6 2250.39  4989.6 2248.02
  5003.8 2247.53  5004.3 2247.03  5015.5 2247.53  5029.6 2251.37  5039.6 2255.59
  5089.6 2263.47  5109.6 2264.05  5139.6 2262.89  5159.6 2265.08  5295.7 2269.53
#Mann= 5 ,-1 , 0
  4329.3     .07       0  4622.9     .16       0  4857.8     .07       0
  5003.8     .07       0  5015.5     .07       0
Bank Sta=5003.8,5015.5
XS Rating Curve= 0 ,0
Exp/Cntr=0.3,0.1

Type RM Length L Ch R = 1 ,10231   ,466,466,466
BEGIN DESCRIPTION:
Bitter Creek Trib8 17.0
END DESCRIPTION:
XS GIS Cut Line= 3
      1427155.03      6831388.02      1426941.38       6831274.8
      1426704.98        6831338.
#Sta/Elev= 30
  4758.2 2258.67  4808.6 2256.98  4848.7 2256.01  4876.4 2254.73  4882.7 2254.31
  4892.7  2251.5  4898.4 2254.01  4905.4    2253  4914.7 2247.61  4920.4 2251.07
    4928 2247.87  4936.7 2245.56  4942.4 2248.43  4958.7 2243.22  4964.4 2244.73
  4974.8 2243.02  4975.3 2242.52  4986.1 2242.52  4986.6 2243.02    5000 2243.45
    5017 2245.28  5026.9 2247.35  5037.7 2250.96  5049.9  2251.6  5079.1 2252.46
  5099.8 2253.68  5107.1 2254.73  5112.2 2254.31  5141.2 2257.04  5244.7  2258.3
#Mann= 5 ,-1 , 0
  4758.2     .07       0  4808.6     .16       0  4974.8     .07       0
  4986.6     .16       0  5049.9     .07       0
Bank Sta=4974.8,4986.6
XS Rating Curve= 0 ,0
Exp/Cntr=0.3,0.1

Type RM Length L Ch R = 1 ,9765    ,482,482,482
BEGIN DESCRIPTION:
Bitter Creek Trib8 16.0
END DESCRIPTION:
XS GIS Cut Line= 3
      1427204.96        6830838.      1426904.05      6830853.39
      1426655.01        6831038.
#Sta/Elev= 30
  4698.7 2257.46  4728.7 2255.06  4738.7 2255.38  4748.7 2254.49  4788.8 2253.04
  4795.2 2251.82  4800.2 2252.67  4808.8 2251.39  4818.8 2251.58  4838.8 2250.92
  4898.9 2245.28  4908.9 2243.77  4987.3 2241.99  4987.8 2241.49  4998.6 2241.49
  4999.1 2241.99    5000 2242.43  5031.4 2243.56  5046.1    2245  5052.3 2248.34
  5066.9 2249.15  5081.5 2250.57  5102.4 2251.23    5117 2252.76  5231.8 2253.88
  5246.4 2254.93  5252.6 2254.73  5281.9 2256.44  5296.5 2256.52    5310 2257.28
#Mann= 3 ,-1 , 0
  4698.7     .07       0  4987.3     .07       0  4999.1     .07       0
Bank Sta=4987.3,4999.1
XS Rating Curve= 0 ,0
Exp/Cntr=0.3,0.1

Type RM Length L Ch R = 1 ,9283    ,407,407,407
BEGIN DESCRIPTION:
Bitter Creek Trib8 15.0
END DESCRIPTION:
XS GIS Cut Line= 3
      1427354.98      6830038.02        1426855.        6830388.
      1426305.03      6830587.99
#Sta/Elev= 30
  4389.7 2295.75  4411.9 2292.95  4438.9 2283.56  4475.1 2274.78  4504.3 2271.73
  4519.1 2273.48  4540.1 2269.14  4626.4 2262.99  4662.1 2252.17    4677 2256.22
  4683.1 2252.82  4706.6  2255.6  4795.6 2249.46  4914.6 2245.99  4927.2 2242.34
  4935.9 2237.14    4942 2236.48  4971.7 2242.82  5002.7 2241.18  5014.2 2235.27
  5014.7 2234.77  5028.4 2235.27  5071.2 2246.76    5127 2245.94  5193.5 2249.78
    5266 2247.58  5301.4 2248.76  5468.2 2254.16  5508.8  2259.9  5585.2 2266.39
#Mann= 5 ,-1 , 0
  4389.7     .07       0  4795.6     .16       0  5014.2     .07       0
  5028.4     .16       0  5301.4     .07       0
Bank Sta=5014.2,5028.4
XS Rating Curve= 0 ,0
Exp/Cntr=0.3,0.1

Type RM Length L Ch R = 1 ,8876    ,498,498,498
BEGIN DESCRIPTION:
Bitter Creek Trib8 14.0
END DESCRIPTION:
XS GIS Cut Line= 3
        1426805.      6829688.01       1426606.7      6830076.98
      1426254.97      6830588.04
#Sta/Elev= 30
  4563.4 2293.43  4599.5 2288.23  4616.2 2281.92  4621.8  2282.4  4630.7 2279.37
  4638.4 2274.84  4653.2 2270.42  4682.9 2265.36  4688.5 2262.32  4698.1 2261.14
  4705.1 2258.48  4742.8 2254.21    4883 2243.76  4956.2 2241.78  4966.3 2239.05
  4971.4 2232.09  4971.9 2231.59  4985.9 2232.09  5003.7 2233.92  5015.6 2237.42
  5037.7 2237.53  5066.7 2242.56  5102.2  2241.7  5218.6 2247.49  5317.3 2246.49
  5389.7 2248.66  5462.5  2252.7    5499 2256.45  5526.3 2261.26  5620.4 2268.99
#Mann= 5 ,-1 , 0
  4563.4     .07       0  4742.8     .16       0  4971.4     .07       0
  4985.9     .16       0  5066.7     .07       0
Bank Sta=4971.4,4985.9
XS Rating Curve= 0 ,0
Exp/Cntr=0.3,0.1