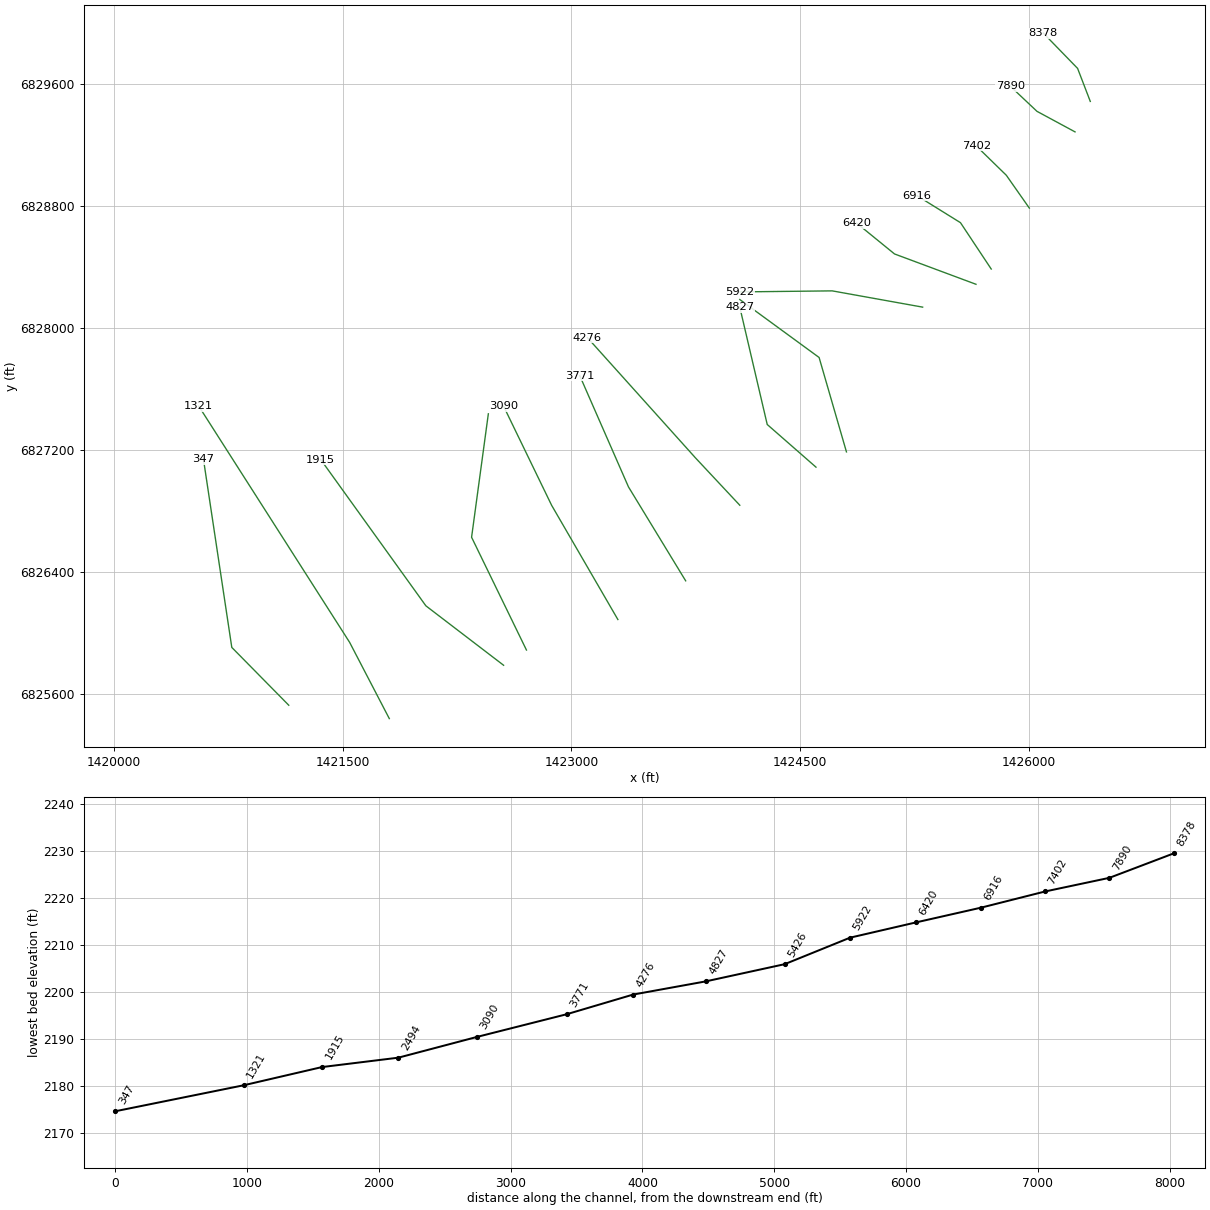
HEC-RAS study Bitter Creek Trib8.prj: Bitter Creek Trib8 Base Level Engineering

--- Bitter Creek Trib8.g01 (geometry) --- (continued)

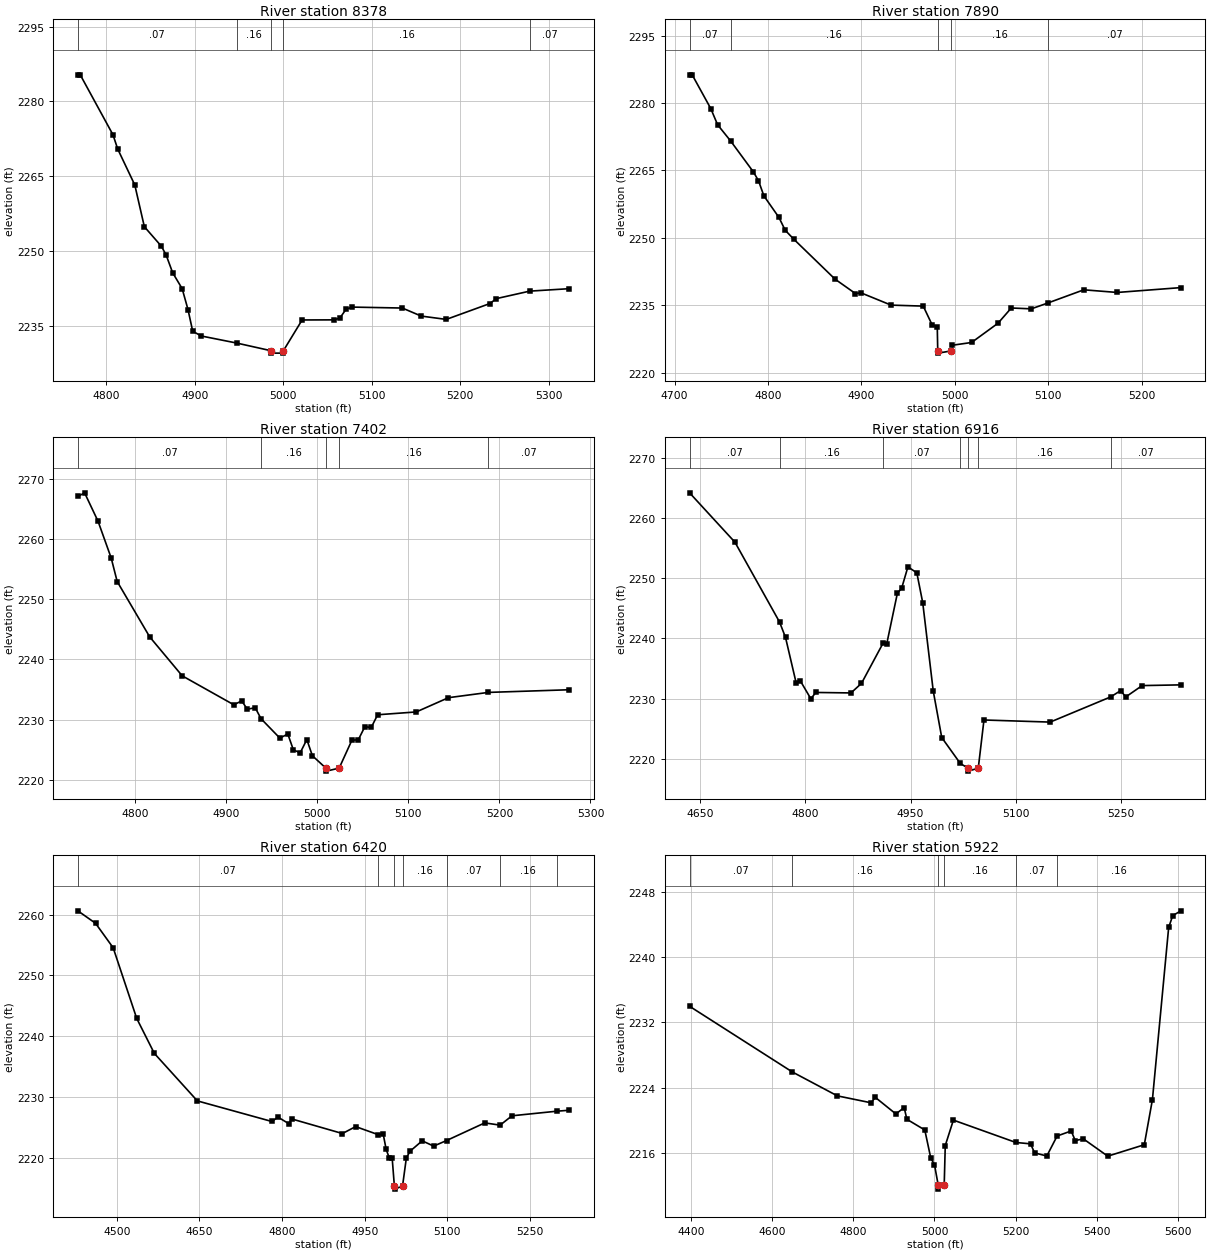
Type RM Length L Ch R = 1 ,8378    ,488,488,488
BEGIN DESCRIPTION:
Bitter Creek Trib8 13.0
END DESCRIPTION:
XS GIS Cut Line= 3
        1426405.      6829487.99      1426321.84      6829704.57
      1426096.83      6829936.17
#Sta/Elev= 30
    4768 2285.34  4770.7 2285.34  4807.7 2273.31    4813 2270.47  4832.3 2263.26
  4843.1 2254.89  4862.4 2250.96  4867.7 2249.21  4875.1 2245.65  4885.8 2242.47
  4892.4 2238.28  4897.7 2233.94  4907.3 2232.98  4947.4 2231.56  4985.7 2230.04
  4986.2 2229.54  4999.7 2229.54  5000.2 2230.04  5021.3 2236.19  5056.8 2236.21
  5063.8 2236.54    5071 2238.35  5077.9 2238.77  5134.5 2238.58  5155.8 2236.97
  5184.1  2236.3  5233.5 2239.49  5240.7 2240.47  5278.3 2241.97  5322.9 2242.46
#Mann= 5 ,-1 , 0
    4768     .07       0  4947.4     .16       0  4985.7     .07       0
  5000.2     .16       0  5278.3     .07       0
Bank Sta=4985.7,5000.2
XS Rating Curve= 0 ,0
Exp/Cntr=0.3,0.1

Type RM Length L Ch R = 1 ,7890    ,488,488,488
BEGIN DESCRIPTION:
Bitter Creek Trib8 12.0
END DESCRIPTION:
XS GIS Cut Line= 3
      1426304.99      6829288.01      1426055.19      6829422.92
      1425879.22       6829588.6
#Sta/Elev= 30
  4716.1  2286.3  4718.9  2286.3  4738.8 2278.78  4746.1 2275.18    4760 2271.58
  4784.2 2264.73  4789.8 2262.75  4795.6 2259.35  4811.7 2254.55  4818.4 2251.69
  4827.9 2249.64  4871.7 2240.81  4893.6 2237.59  4899.3 2237.77  4931.7 2235.02
  4966.1  2234.8  4975.5 2230.67  4981.1 2230.19  4981.6 2224.83  4982.1 2224.33
  4996.1 2224.83  4997.3 2226.09  5017.8  2226.7  5046.1 2230.99  5060.3 2234.38
  5081.7 2234.19  5099.9 2235.53  5137.9 2238.43  5173.6 2237.84  5241.7 2238.92
#Mann= 5 ,-1 , 0
  4716.1     .07       0    4760     .16       0  4981.6     .07       0
  4996.1     .16       0  5099.9     .07       0
Bank Sta=4981.6,4996.1
XS Rating Curve= 0 ,0
Exp/Cntr=0.3,0.1

Type RM Length L Ch R = 1 ,7402    ,486,486,486
BEGIN DESCRIPTION:
Bitter Creek Trib8 11.0
END DESCRIPTION:
XS GIS Cut Line= 3
        1426005.        6828788.      1425854.06      6829003.38
      1425656.11      6829196.56
#Sta/Elev= 30
    4737 2267.12  4744.4 2267.73  4759.2 2262.99  4773.6 2256.89  4780.2 2252.97
  4815.9 2243.76  4851.6 2237.28  4908.3 2232.46    4917 2233.11  4923.1 2231.72
  4931.8 2231.97  4938.2 2230.14  4958.9 2226.91  4967.6  2227.6  4973.7 2224.96
  4981.2 2224.47  4988.5 2226.67  4994.6 2223.98  5009.4 2221.92  5009.9 2221.42
    5024 2221.92    5038 2226.57    5045 2226.63  5052.2 2228.81  5059.2 2228.68
  5066.3  2230.8  5108.7 2231.27    5144 2233.64  5187.9 2234.52  5276.6 2234.96
#Mann= 5 ,-1 , 0
    4737     .07       0  4938.2     .16       0  5009.4     .07       0
    5024     .16       0  5187.9     .07       0
Bank Sta=5009.4,5024
XS Rating Curve= 0 ,0
Exp/Cntr=0.3,0.1

Type RM Length L Ch R = 1 ,6916    ,496,496,496
BEGIN DESCRIPTION:
Bitter Creek Trib8 10.0
END DESCRIPTION:
XS GIS Cut Line= 3
        1425755.        6828388.      1425553.27      6828692.19
      1425268.35      6828869.15
#Sta/Elev= 30
    4635 2264.17  4699.7 2255.97  4763.3 2242.72  4771.8 2240.16  4786.9 2232.64
  4792.9 2232.96  4807.9 2229.98    4815 2231.03  4865.1 2230.95  4880.1 2232.54
  4911.3 2239.31  4916.2 2239.15  4931.3 2247.52  4937.3 2248.31  4946.3 2251.89
    4959 2250.88  4967.4 2245.94  4982.4 2231.27  4994.5 2223.55    5021 2219.24
    5032 2218.47  5032.5 2217.97  5046.6 2218.47  5054.7 2226.46  5149.1 2226.11
  5235.3 2230.29  5249.5 2231.33  5256.9 2230.29  5280.2 2232.17  5335.4 2232.29
#Mann= 7 ,-1 , 0
    4635     .07       0  4763.3     .16       0  4911.3     .07       0
    5021     .16       0    5032     .07       0  5046.6     .16       0
  5235.3     .07       0
Bank Sta=5032,5046.6
XS Rating Curve= 0 ,0
Exp/Cntr=0.3,0.1

Type RM Length L Ch R = 1 ,6420    ,498,498,498
BEGIN DESCRIPTION:
Bitter Creek Trib8 9.0
END DESCRIPTION:
XS GIS Cut Line= 3
      1425655.04      6828287.98       1425120.4      6828487.04
       1424871.3      6828689.82
#Sta/Elev= 30
  4429.5 2260.61  4461.6 2258.56  4493.6 2254.53  4536.3 2242.91  4568.3 2237.15
  4646.4 2229.33  4781.7 2225.94  4792.7 2226.66  4812.4 2225.58  4817.7 2226.36
  4909.7 2223.96  4933.7  2225.1  4974.2 2223.79  4983.7 2223.88  4989.1 2221.34
  4994.9 2219.92    5000 2219.92    5004 2215.31  5004.5 2214.81  5018.8 2215.31
  5025.8 2219.98  5032.7 2221.07  5054.5 2222.76  5075.3 2221.89  5098.8 2222.81
    5168 2225.71  5195.9 2225.34  5217.5 2226.88  5298.3 2227.63  5321.2 2227.79
#Mann= 7 ,-1 , 0
  4429.5     .07       0  4974.2     .16       0    5004     .07       0
  5018.8     .16       0  5098.8     .07       0  5195.9     .16       0
  5298.3     .07       0
Bank Sta=5004,5018.8
XS Rating Curve= 0 ,0
Exp/Cntr=0.3,0.1

Type RM Length L Ch R = 1 ,5922    ,496,496,496
BEGIN DESCRIPTION:
Bitter Creek Trib8 8.0
END DESCRIPTION:
XS GIS Cut Line= 3
      1425304.96      6828138.01      1424711.48      6828244.76
      1424105.02        6828238.
#Sta/Elev= 30
    4397 2233.98    4650 2225.93  4760.9    2223    4844 2222.15  4854.2 2222.82
    4905 2220.78  4925.3 2221.57    4932 2220.13  4976.1 2218.82  4990.7 2215.41
    5000 2214.55  5009.1 2212.07  5009.6 2211.57  5023.9 2212.07  5026.5 2216.91
  5046.5 2220.03  5200.2 2217.29  5236.5 2217.12  5246.5 2216.01  5276.5 2215.63
  5301.9 2218.08  5336.5  2218.7  5346.5 2217.52  5366.5 2217.73  5426.5 2215.61
  5516.5 2217.01  5536.5 2222.54  5576.5 2243.64  5586.5 2245.09  5606.5 2245.68
#Mann= 6 ,-1 , 0
    4397     .07       0    4650     .16       0  5009.1     .07       0
  5023.9     .16       0  5200.2     .07       0  5301.9     .16       0
Bank Sta=5009.1,5023.9
XS Rating Curve= 0 ,0
Exp/Cntr=0.3,0.1

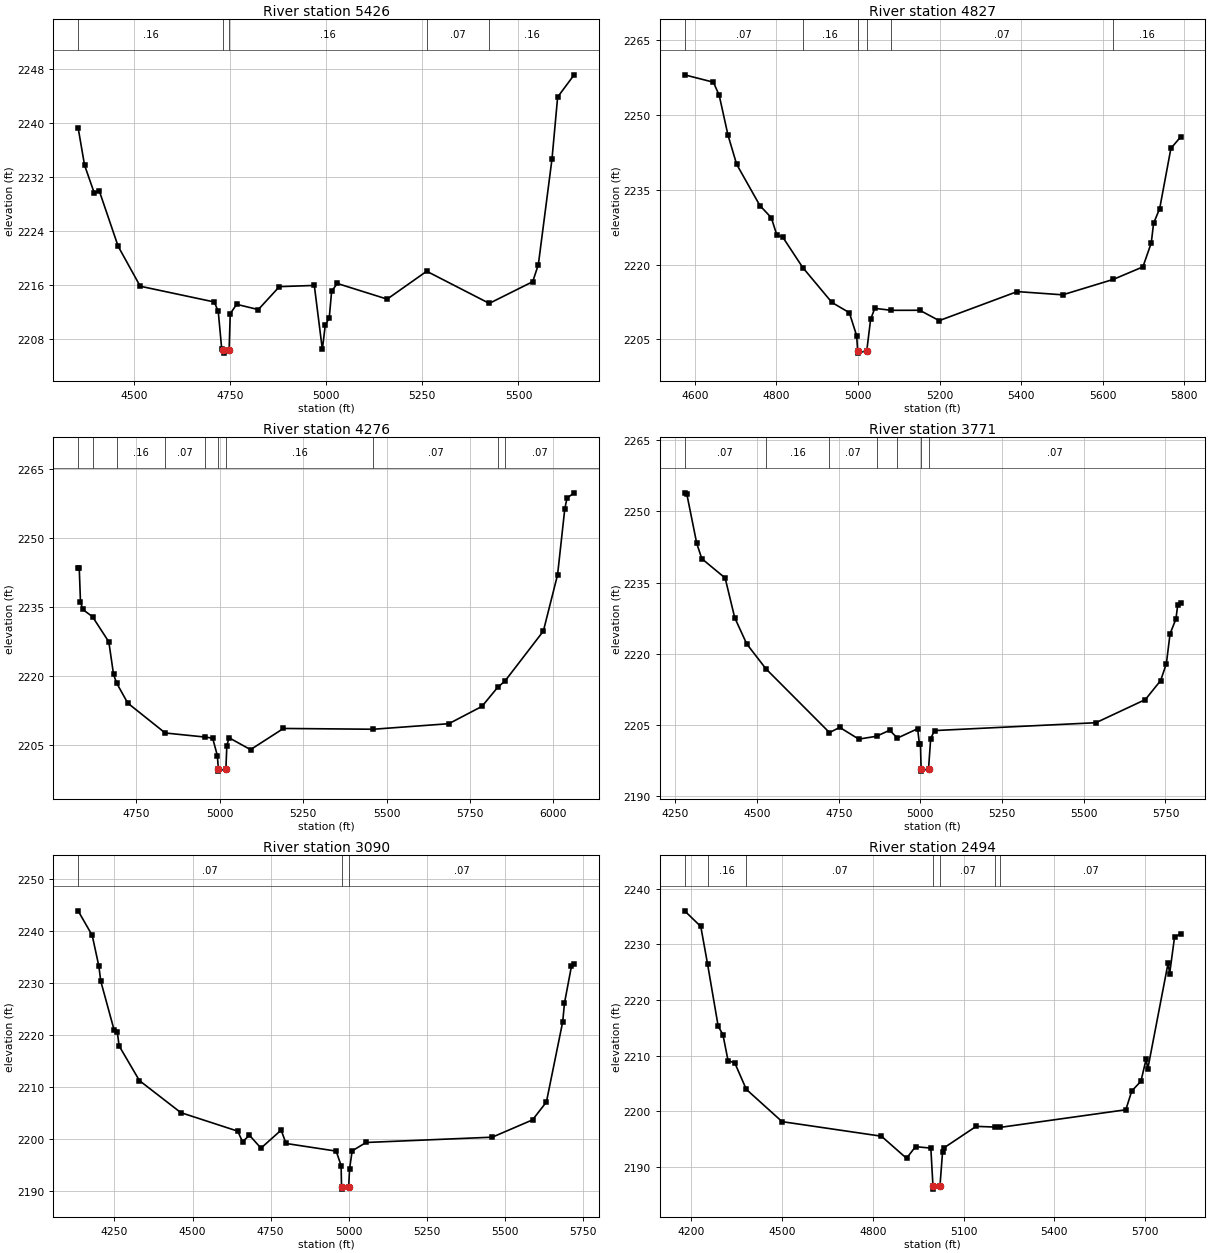
Type RM Length L Ch R = 1 ,5426    ,599,599,599
BEGIN DESCRIPTION:
Bitter Creek Trib8 7.0
END DESCRIPTION:
XS GIS Cut Line= 3
        1424805.      6827188.01      1424625.48      6827807.63
      1424104.96      6828188.03
#Sta/Elev= 30
  4354.9 2239.33  4371.7 2233.77  4396.5 2229.71  4410.5 2229.87    4459 2221.75
  4516.4 2215.83  4708.9  2213.5  4719.3  2212.1  4728.3 2206.56  4732.7 2206.42
  4733.2 2205.92  4747.6 2206.42  4750.5 2211.76  4767.1 2213.15  4823.4 2212.37
  4878.3 2215.77  4969.1 2215.95    4990 2206.46  4997.6 2210.09  5007.9 2211.12
  5014.1 2215.08  5028.8 2216.24  5158.5 2213.92  5261.3 2218.05    5424 2213.29
  5536.9  2216.5  5551.6 2219.03  5587.1 2234.68  5601.8 2243.86  5644.7 2247.15
#Mann= 5 ,-1 , 0
  4354.9     .16       0  4732.7     .07       0  4747.6     .16       0
  5261.3     .07       0    5424     .16       0
Bank Sta=4732.7,4747.6
XS Rating Curve= 0 ,0
Exp/Cntr=0.3,0.1

Type RM Length L Ch R = 1 ,4827    ,551,551,551
BEGIN DESCRIPTION:
Bitter Creek Trib8 6.0
END DESCRIPTION:
XS GIS Cut Line= 3
      1424605.03      6827087.97      1424285.02      6827367.95
        1424105.      6828137.99
#Sta/Elev= 30
  4574.8  2258.1  4645.5 2256.62  4659.8 2253.96  4681.1 2246.05  4702.5 2240.14
  4759.4 2231.87  4787.4 2229.43  4801.2 2225.91  4815.4 2225.54  4864.6 2219.42
    4936 2212.42  4978.7 2210.37  4996.7 2205.73  4999.1 2202.75  4999.6 2202.25
  5021.5 2202.75  5030.9 2209.03  5041.1 2211.24  5081.6 2210.84  5151.4 2210.85
    5199 2208.77  5390.3  2214.6  5501.7 2213.95  5625.6 2217.04  5698.4 2219.56
  5718.9 2224.39  5724.5 2228.29  5739.5 2231.26    5767 2243.34  5790.8 2245.63
#Mann= 6 ,-1 , 0
  4574.8     .07       0  4864.6     .16       0  4999.1     .07       0
  5021.5     .16       0  5081.6     .07       0  5625.6     .16       0
Bank Sta=4999.1,5021.5
XS Rating Curve= 0 ,0
Exp/Cntr=0.3,0.1

Type RM Length L Ch R = 1 ,4276    ,505,505,505
BEGIN DESCRIPTION:
Bitter Creek Trib8 5.0
END DESCRIPTION:
XS GIS Cut Line= 3
      1424105.02      6826837.98      1423815.05      6827147.88
        1423105.        6827938.
#Sta/Elev= 30
  4575.6 2243.42  4579.1 2243.42  4582.7 2236.19  4589.6 2234.48  4618.8 2232.92
  4667.7 2227.46  4681.9 2220.39  4691.3  2218.5  4724.4 2214.19  4836.7 2207.71
  4956.6 2206.82  4978.9 2206.58    4993 2202.81  4995.9 2199.94  4996.4 2199.44
  5018.6 2199.94  5021.4 2204.99  5028.1 2206.67  5092.4  2204.1  5191.1 2208.69
  5460.5 2208.52  5686.7 2209.72  5786.1 2213.48  5833.4 2217.63  5854.6 2218.93
    5970 2229.79  6012.6 2241.99  6034.3 2256.32    6041 2258.63  6062.3 2259.77
#Mann= 10 ,-1 , 0
  4575.6     .16       0  4618.8     .07       0  4691.3     .16       0
  4836.7     .07       0  4956.6     .16       0  4995.9     .07       0
  5018.6     .16       0  5460.5     .07       0  5833.4     .16       0
  5854.6     .07       0
Bank Sta=4995.9,5018.6
XS Rating Curve= 0 ,0
Exp/Cntr=0.3,0.1

Type RM Length L Ch R = 1 ,3771    ,681,681,681
BEGIN DESCRIPTION:
Bitter Creek Trib8 4.0
END DESCRIPTION:
XS GIS Cut Line= 3
      1423749.88      6826341.94      1423374.47      6826958.54
      1423055.02      6827687.96
#Sta/Elev= 30
  4278.1 2253.92  4285.2  2253.6  4315.4 2243.25  4330.9 2240.03  4402.3 2235.96
  4431.6 2227.59  4468.4 2222.06  4527.3  2216.8  4721.6 2203.37  4753.1 2204.46
  4811.2 2201.99  4865.6 2202.59  4905.7 2203.86  4929.6 2202.21  4991.4 2204.18
  4996.8 2201.04    5000 2201.04  5002.1 2195.74  5002.6 2195.24  5024.8 2195.74
  5031.4 2202.11  5043.1 2203.79  5537.2 2205.45  5688.4 2210.33  5735.2 2214.34
  5752.7  2217.9    5764  2224.2  5781.9  2227.3  5787.4 2230.25  5796.3  2230.7
#Mann= 7 ,-1 , 0
  4278.1     .07       0  4527.3     .16       0  4721.6     .07       0
  4865.6     .16       0  4929.6     .07       0  5002.1     .07       0
  5024.8     .07       0
Bank Sta=5002.1,5024.8
XS Rating Curve= 0 ,0
Exp/Cntr=0.3,0.1

Type RM Length L Ch R = 1 ,3090    ,596,596,596
BEGIN DESCRIPTION:
Bitter Creek Trib8 3.0
END DESCRIPTION:
XS GIS Cut Line= 3
      1423305.01      6826087.98      1422870.27      6826837.64
      1422555.02      6827487.96
#Sta/Elev= 30
  4133.4 2243.92  4178.6  2239.2  4200.1 2233.23  4205.9 2230.43    4249 2220.95
  4258.9 2220.71  4264.7 2217.96  4329.9 2211.27  4462.6 2205.11  4644.8 2201.55
  4660.5 2199.48  4682.1 2200.78  4719.3 2198.28  4783.9 2201.75  4799.7 2199.18
  4960.3 2197.71  4976.1 2194.92  4977.4  2190.9  4977.9  2190.4  5000.3  2190.9
  5003.3 2194.35  5011.5 2197.76    5056 2199.37  5460.4 2200.39  5589.4 2203.72
  5633.8 2207.15  5686.1 2222.59  5691.7 2226.17  5714.2 2233.31  5722.7 2233.72
#Mann= 3 ,-1 , 0
  4133.4     .07       0  4977.4     .07       0  5000.3     .07       0
Bank Sta=4977.4,5000.3
XS Rating Curve= 0 ,0
Exp/Cntr=0.3,0.1

Type RM Length L Ch R = 1 ,2494    ,579,579,579
BEGIN DESCRIPTION:
Bitter Creek Trib8 2.0
END DESCRIPTION:
XS GIS Cut Line= 3
      1422705.01      6825887.98      1422345.02      6826627.85
        1422455.      6827438.02
#Sta/Elev= 30
  4177.2 2236.05  4230.8 2233.24  4253.2  2226.5  4288.4 2215.28    4304 2213.79
    4321 2209.11  4343.6 2208.65  4381.4 2203.93  4499.7 2198.12  4828.2  2195.5
  4911.2 2191.53    4941 2193.62  4991.6 2193.36  4998.7 2186.48  4999.2 2185.98
  5021.7 2186.48  5030.4 2192.69  5036.3 2193.45  5141.4 2197.27  5203.8 2197.15
    5221 2197.09  5636.4 2200.26  5656.1 2203.64  5686.4 2205.39  5703.8 2209.42
  5708.8 2207.55  5776.3 2226.67  5781.3 2224.71  5797.4 2231.29  5817.6 2231.96
#Mann= 7 ,-1 , 0
  4177.2     .07       0  4253.2     .16       0  4381.4     .07       0
  4998.7     .07       0  5021.7     .07       0  5203.8     .16       0
    5221     .07       0
Bank Sta=4998.7,5021.7
XS Rating Curve= 0 ,0
Exp/Cntr=0.3,0.1

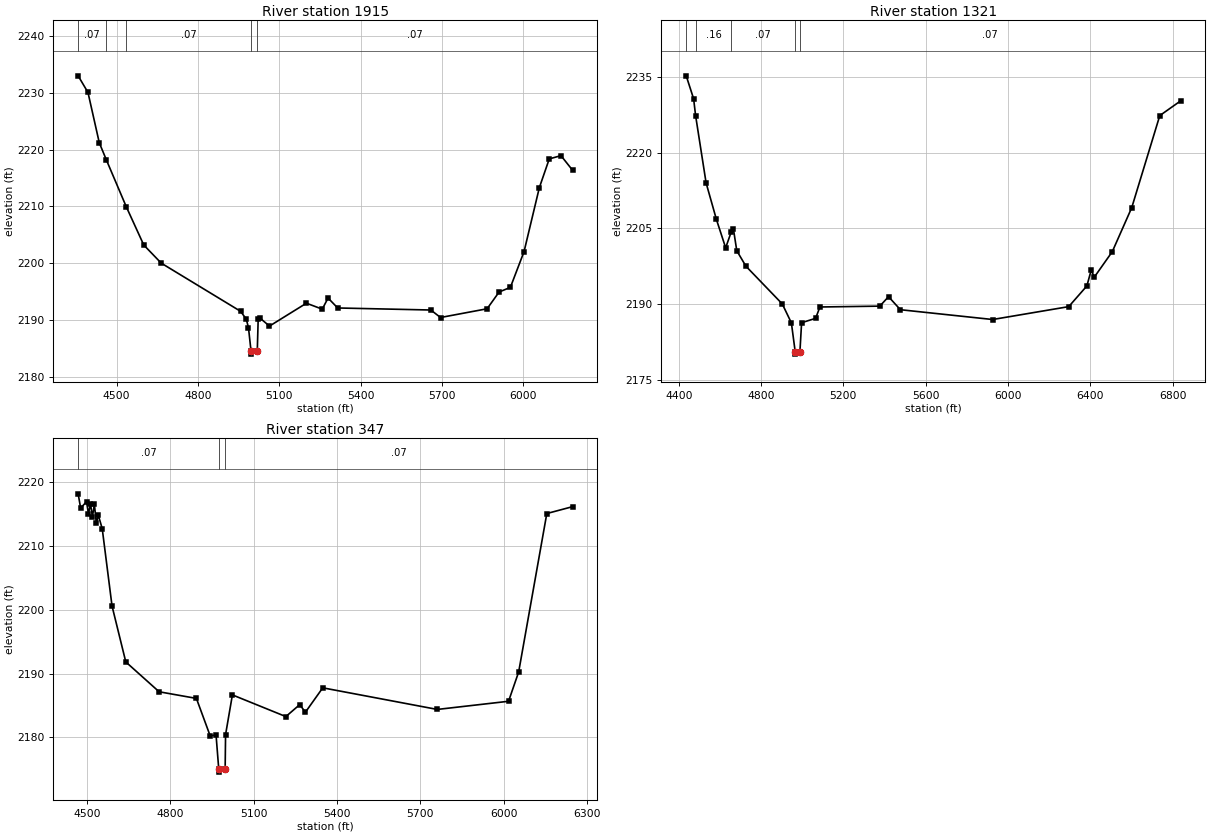
Type RM Length L Ch R = 1 ,1915    ,594,594,594
BEGIN DESCRIPTION:
Bitter Creek Trib8 1.0
END DESCRIPTION:
XS GIS Cut Line= 3
      1422555.02      6825787.98      1422045.14      6826177.92
      1421354.99      6827138.01
#Sta/Elev= 30
  4358.1    2233  4394.4 2230.07  4436.1 2221.21  4461.9 2218.23  4535.4 2209.97
  4600.2  2203.2  4664.6 2200.01  4957.5 2191.52  4978.4 2190.14  4986.6 2188.62
    4996 2184.48  4996.5 2183.98    5019 2184.48  5022.3 2190.13  5028.4 2190.35
    5064 2188.92  5200.3 2192.95  5258.7  2191.9  5280.1 2193.86  5315.7 2192.11
  5659.4 2191.75    5695 2190.43  5866.9 2191.97  5911.1 2194.92  5952.8 2195.74
  6003.2 2202.04  6059.6  2213.3  6096.2 2218.37  6139.4 2218.94  6182.4 2216.36
#Mann= 5 ,-1 , 0
  4358.1     .07       0  4461.9     .16       0  4535.4     .07       0
    4996     .07       0    5019     .07       0
Bank Sta=4996,5019
XS Rating Curve= 0 ,0
Exp/Cntr=0.3,0.1

Type RM Length L Ch R = 1 ,1321    ,974,974,974
BEGIN DESCRIPTION:
Bitter Creek Trib8 0.1
END DESCRIPTION:
XS GIS Cut Line= 3
      1421805.01      6825437.98      1421544.95      6825937.88
      1420554.98      6827488.03
#Sta/Elev= 30
  4436.5 2235.18  4472.5 2230.64  4482.2 2227.29  4533.2 2213.98  4583.1 2206.78
  4628.2 2201.14  4655.2 2204.28  4665.8 2204.89  4682.3 2200.56  4726.5 2197.51
  4903.4 2190.03  4947.6 2186.28    4966  2180.6  4966.5  2180.1  4989.1  2180.6
  4997.2 2186.32  5065.2 2187.18  5086.3 2189.43  5377.3  2189.6  5419.7 2191.47
  5477.2 2188.89  5925.6 2186.95  6295.3  2189.5  6383.3 2193.59  6404.4 2196.72
  6419.6 2195.34    6507 2200.39  6601.5  2209.1  6737.7 2227.31  6839.3 2230.23
#Mann= 5 ,-1 , 0
  4436.5     .07       0  4482.2     .16       0  4655.2     .07       0
    4966     .07       0  4989.1     .07       0
Bank Sta=4966,4989.1
XS Rating Curve= 0 ,0
Exp/Cntr=0.3,0.1

Type RM Length L Ch R = 1 ,347     ,0,0,0
BEGIN DESCRIPTION:
Bitter Creek Trib8 4167
END DESCRIPTION:
XS GIS Cut Line= 3
      1421145.32      6825525.64      1420771.47      6825905.12
      1420585.44      6827140.19
#Sta/Elev= 30
  4467.3  2218.2  4476.3 2215.97  4497.5 2216.96  4504.5 2215.08  4511.7 2216.67
  4518.7 2214.58  4525.8 2216.58  4532.8 2213.58    4540 2214.85  4554.1 2212.73
  4589.4 2200.61    4639 2191.84  4759.1 2187.16  4893.4 2186.12    4943 2180.25
  4964.2 2180.39  4973.9 2175.06  4974.4 2174.56    4997 2175.06  4998.5 2180.44
  5023.1 2186.67  5215.8 2183.27  5265.8 2185.15  5286.1 2183.95  5348.7 2187.78
  5761.4 2184.39  6018.1 2185.67  6054.6 2190.27    6156 2215.11    6249 2216.19
#Mann= 3 ,-1 , 0
  4467.3     .07       0  4973.9     .07       0    4997     .07       0
Bank Sta=4973.9,4997
XS Rating Curve= 0 ,0
Exp/Cntr=0.3,0.1

Chan Stop Cuts=-1
Use User Specified Reach Order=0
Composite Channel Slope=5