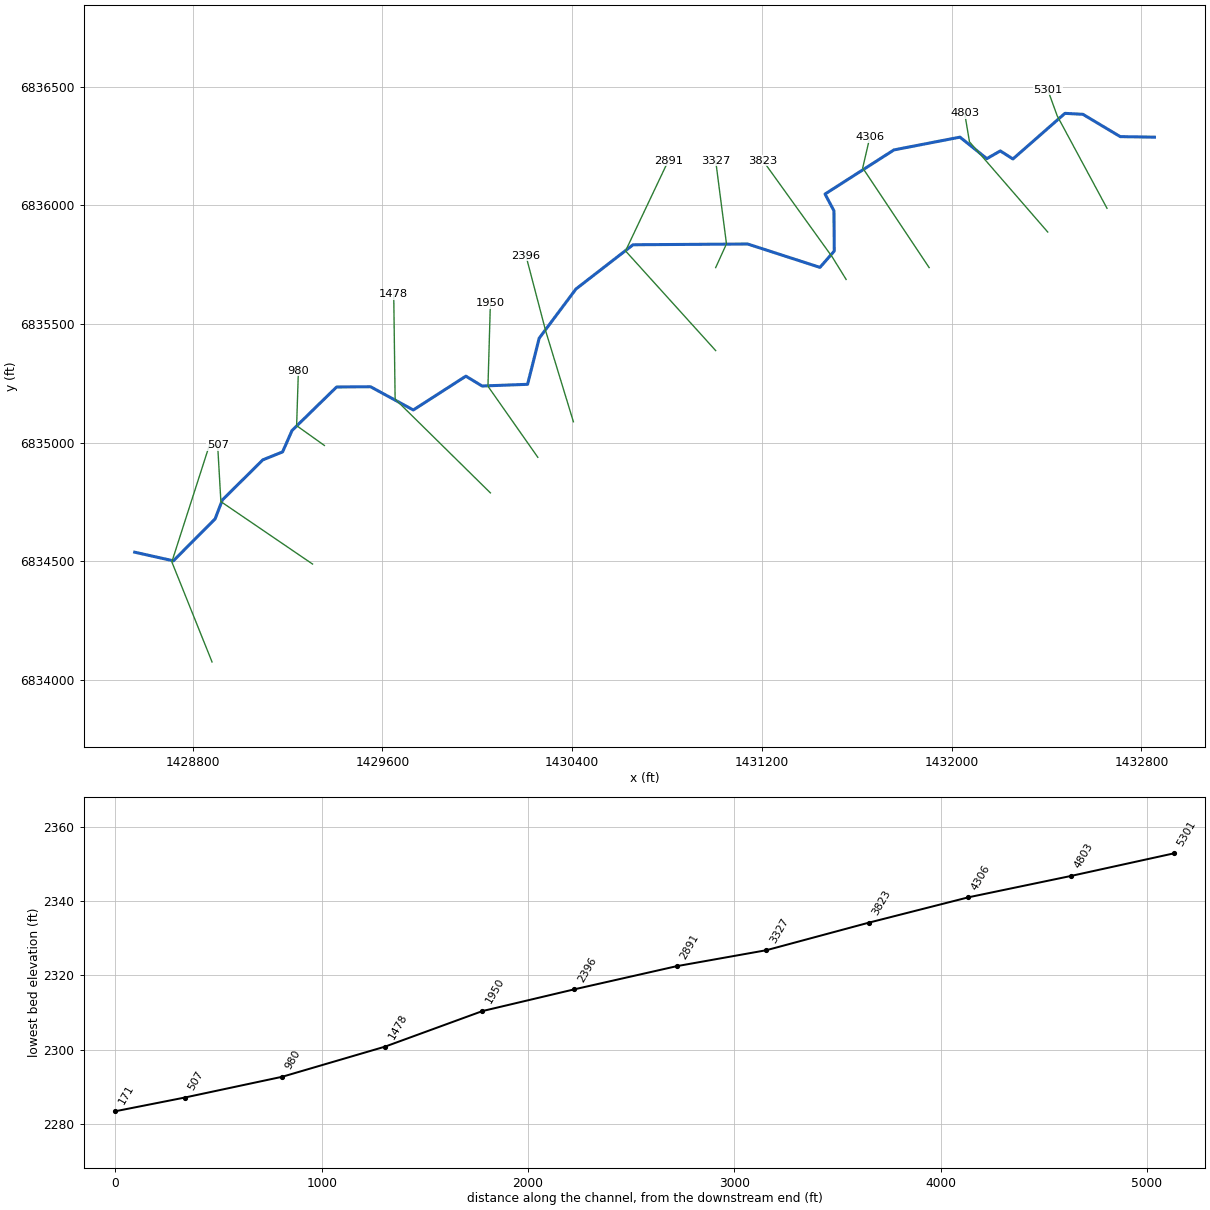
--- Bitter Creek Trib8T1.prj (project) ---

Proj Title=Bitter Creek Trib8T1 Base Level Engineering
Current Plan=p01
Default Exp/Contr=0.3,0.1
English Units
Geom File=g01
Flow File=f01
Plan File=p01
Y Axis Title=Elevation
X Axis Title(PF)=Main Channel Distance
X Axis Title(XS)=Station
BEGIN DESCRIPTION:
Bitter Creek Trib8T1
END DESCRIPTION:
DSS Export Rating Curves= 0
DSS Export Rating Curve Sorted= 0
DSS Export Volume Flow Curves= 0
DXF OffsetX= 0
DXF OffsetY= 0
DXF ScaleX= 1
DXF ScaleY= 10

--- Bitter Creek Trib8T1.p01 (plan) ---

Plan Title=Multiple Run
Short Identifier=Multiple
Geom File=g01
Flow File=f01
Subcritical Flow
K Sum by GR= 0
Std Step Tol= 0.01
Critical Tol= 0.01
Num of Std Step Trials= 20
Max Error Tol= 0.3
Flow Tol Ratio= 0.001
Split Flow NTrial= 30
Split Flow Tol= 0.02
Split Flow Ratio= 0.02
Log Output Level= 0
Friction Slope Method= 1
Unsteady Friction Slope Method= 2
Unsteady Bridges Friction Slope Method= 1
Parabolic Critical Depth
Global Vel Dist=  1 , 1 , 1
Global Log Level= 0
CheckData=True
Encroach Param= -1, 0, 0, 0
BEGIN DESCRIPTION:
Multiple Run
END DESCRIPTION:

--- Bitter Creek Trib8T1.f01 (steady flow) ---

Flow Title=Multiple
Number of Profiles=7
Profile Names=10-year,25-year,50-year,1pct_min,100-year,1pct_plu,500-year
River Rch & RM= Bitter Creek Tri,Reach-1,5301
     479     702     895     568    1134    2263    1841
Boundary for River Rch & Prof#=Bitter Creek Tri,Reach-1,1
Up Type=0
Dn Type=3
Dn Slope=0.005
Boundary for River Rch & Prof#=Bitter Creek Tri,Reach-1,2
Up Type=0
Dn Type=3
Dn Slope=0.005
Boundary for River Rch & Prof#=Bitter Creek Tri,Reach-1,3
Up Type=0
Dn Type=3
Dn Slope=0.005
Boundary for River Rch & Prof#=Bitter Creek Tri,Reach-1,4
Up Type=0
Dn Type=3
Dn Slope=0.005
Boundary for River Rch & Prof#=Bitter Creek Tri,Reach-1,5
Up Type=0
Dn Type=3
Dn Slope=0.005
Boundary for River Rch & Prof#=Bitter Creek Tri,Reach-1,6
Up Type=0
Dn Type=3
Dn Slope=0.005
Boundary for River Rch & Prof#=Bitter Creek Tri,Reach-1,7
Up Type=0
Dn Type=3
Dn Slope=0.005

--- Bitter Creek Trib8T1.g01 (geometry) ---

Geom Title=Existing Conditions

River Reach=Bitter Creek Tri,Reach-1
Reach XY= 30
      1432855.00      6836288.00      1432710.91      6836290.20
      1432553.41      6836384.33      1432477.72      6836388.38
      1432258.33      6836195.98      1432205.00      6836229.95
      1432148.34      6836197.31      1432035.01      6836288.05
      1431756.58      6836234.17      1431466.09      6836048.08
      1431503.61      6835977.57      1431505.09      6835807.87
      1431444.69      6835738.86      1431139.78      6835837.48
      1430656.55      6835834.25      1430415.78      6835647.68
      1430260.81      6835440.29      1430211.82      6835245.81
      1430020.16      6835238.66      1429951.59      6835280.19
      1429730.00      6835137.58      1429549.48      6835235.66
      1429406.47      6835234.47      1429218.64      6835051.20
      1429178.84      6834960.86      1429095.34      6834927.21
      1428924.79      6834758.09      1428894.22      6834678.32
      1428718.38      6834501.51      1428555.00      6834538.00

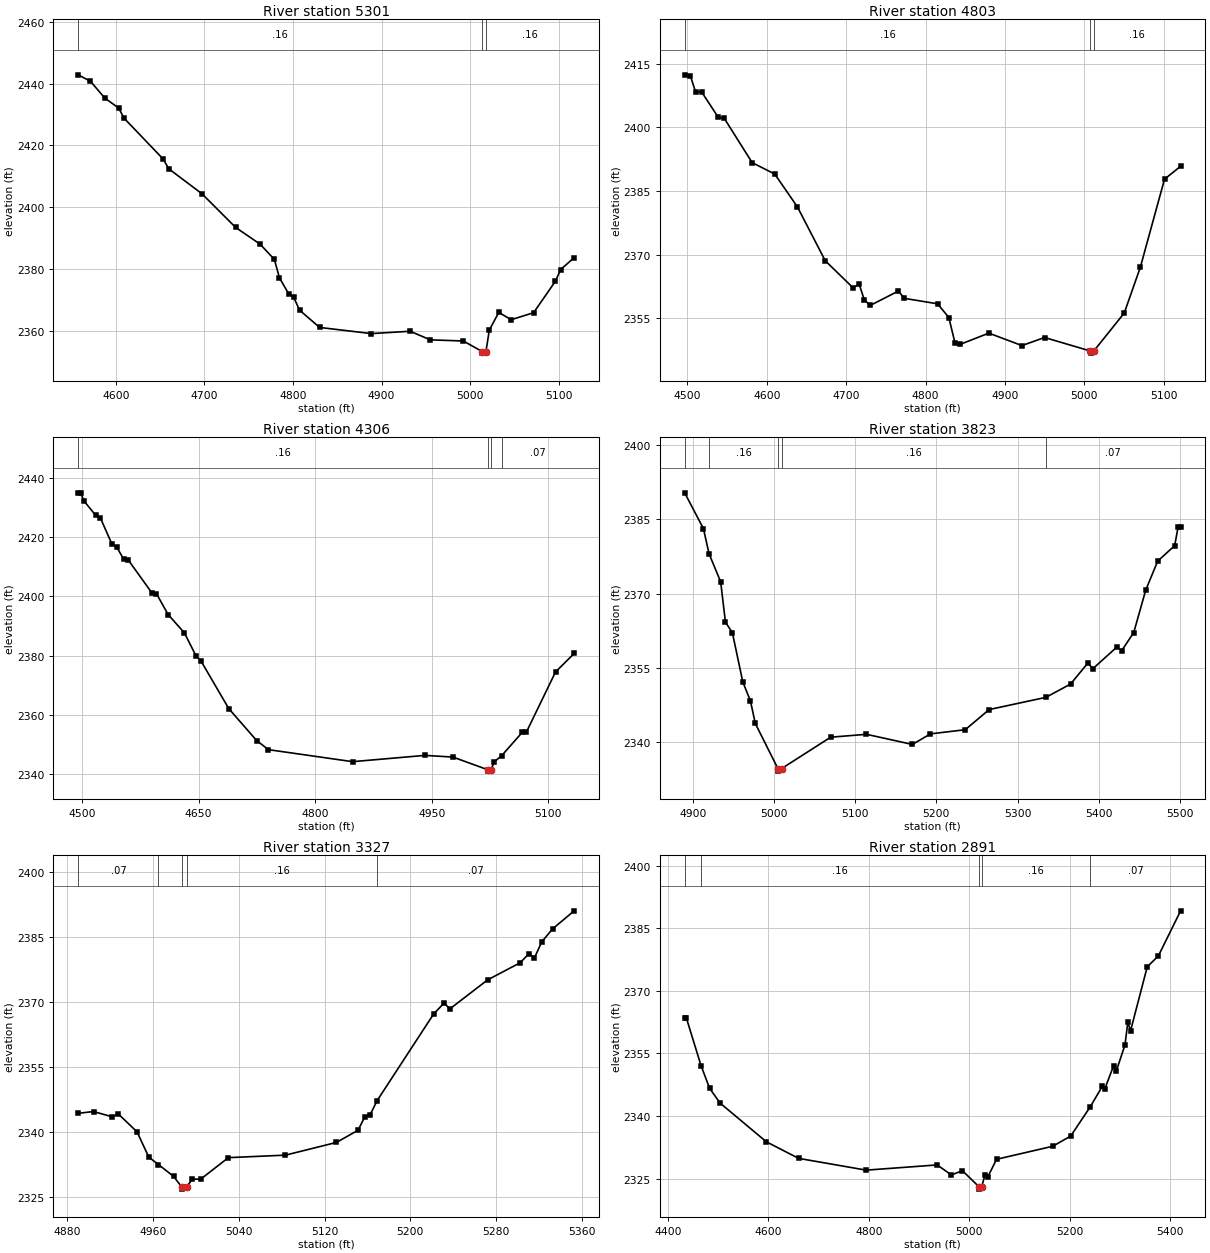
Type RM Length L Ch R = 1,5301,498,498,498
BEGIN DESCRIPTION:
Bitter Creek Trib8T1 10.0
END DESCRIPTION:
XS GIS Cut Line= 3
      1432655.02      6835987.97      1432445.21      6836377.57
      1432405.01      6836487.97
#Sta/Elev= 30
  4557.5 2442.83  4571.3 2440.75  4587.6 2435.29  4603.0 2432.14  4609.5 2428.75
  4653.3 2415.65  4659.8 2412.46  4697.1 2404.43  4735.2 2393.53  4762.8 2388.13
  4779.0 2383.19  4784.7 2377.25  4795.2 2372.03  4800.9 2370.91  4807.4 2366.79
  4830.1 2361.20  4888.5 2359.21  4932.3 2359.97  4955.1 2357.19  4992.4 2356.82
  5013.7 2353.40  5014.0 2352.90  5017.9 2353.40  5021.7 2360.35  5032.4 2366.06
  5046.4 2363.70  5071.7 2365.96  5096.2 2376.07  5102.2 2379.89  5117.5 2383.76
#Mann=3,-1,0
  4557.5    0.16       0  5013.7    0.07       0  5017.9    0.16       0
Bank Sta=5013.7,5017.9
Exp/Cntr=0.3,0.1

Type RM Length L Ch R = 1,4803,497,497,497
BEGIN DESCRIPTION:
Bitter Creek Trib8T1 9.0
END DESCRIPTION:
XS GIS Cut Line= 3
      1432404.99      6835888.01      1432075.16      6836268.31
      1432055.00      6836388.02
#Sta/Elev= 30
  4496.6 2412.38  4503.7 2412.21  4510.3 2408.36  4518.0 2408.34  4538.8 2402.41
  4546.5 2402.12  4581.6 2391.70  4610.1 2389.00  4638.6 2381.28  4673.7 2368.58
  4708.8 2362.20  4716.4 2363.07  4723.1 2359.26  4730.7 2358.09  4765.8 2361.44
  4773.4 2359.72  4815.2 2358.44  4829.4 2355.21  4837.1 2349.24  4843.7 2348.89
  4879.8 2351.53  4921.5 2348.60  4950.0 2350.50  5007.7 2347.32  5008.0 2346.82
  5012.0 2347.32  5050.4 2356.27  5070.7 2367.08  5101.1 2387.79  5121.4 2390.84
#Mann=3,-1,0
  4496.6    0.16       0  5007.7    0.07       0  5012.0    0.16       0
Bank Sta=5007.7,5012
Exp/Cntr=0.3,0.1

Type RM Length L Ch R = 1,4306,483,483,483
BEGIN DESCRIPTION:
Bitter Creek Trib8T1 8.0
END DESCRIPTION:
XS GIS Cut Line= 3
      1431905.02      6835737.97      1431624.92      6836158.18
      1431655.01      6836288.04
#Sta/Elev= 30
  4495.0 2434.94  4498.0 2434.94  4502.5 2432.16  4517.6 2427.32  4523.6 2426.43
  4538.6 2417.54  4544.6 2416.65  4553.6 2412.48  4559.6 2412.22  4589.7 2401.22
  4595.7 2400.92  4610.7 2393.89  4631.7 2387.68  4646.8 2379.84  4652.8 2378.31
  4688.8 2362.14  4724.9 2351.31  4739.9 2348.30  4848.1 2344.25  4941.2 2346.37
  4977.3 2345.80  5021.8 2341.56  5022.1 2341.06  5026.2 2341.56  5030.6 2344.22
  5040.1 2346.30  5066.7 2354.20  5071.8 2354.21  5109.3 2374.50  5133.3 2380.75
#Mann=4,-1,0
  4495.0    0.16       0  5021.8    0.07       0  5026.2    0.16       0
  5040.1    0.07       0
Bank Sta=5021.8,5026.2
Exp/Cntr=0.3,0.1

Type RM Length L Ch R = 1,3823,496,496,496
BEGIN DESCRIPTION:
Bitter Creek Trib8T1 7.0
END DESCRIPTION:
XS GIS Cut Line= 3
      1431554.98      6835688.03      1431497.33      6835781.47
      1431205.01      6836187.98
#Sta/Elev= 30
  4890.2 2390.32  4913.3 2383.10  4920.2 2378.04  4934.5 2372.38  4940.4 2364.24
  4948.9 2362.14  4961.7 2352.23  4971.2 2348.34  4977.1 2343.84  5005.0 2334.72
  5005.3 2334.22  5009.4 2334.72  5069.9 2341.06  5114.0 2341.64  5170.5 2339.60
  5192.8 2341.73  5235.6 2342.57  5265.0 2346.63  5334.8 2349.09  5365.2 2351.77
  5386.5 2356.00  5392.7 2354.87  5422.1 2359.22  5428.3 2358.53  5443.0 2362.16
  5457.8 2370.74  5472.5 2376.56  5493.4 2379.67  5497.6 2383.45  5500.7 2383.45
#Mann=5,-1,0
  4890.2    0.07       0  4920.2    0.16       0  5005.0    0.07       0
  5009.4    0.16       0  5334.8    0.07       0
Bank Sta=5005,5009.4
Exp/Cntr=0.3,0.1

Type RM Length L Ch R = 1,3327,436,436,436
BEGIN DESCRIPTION:
Bitter Creek Trib8T1 6.0
END DESCRIPTION:
XS GIS Cut Line= 3
      1431005.01      6835738.01      1431050.48      6835838.06
      1431005.00      6836188.02
#Sta/Elev= 30
  4890.1 2344.31  4904.4 2344.72  4921.9 2343.50  4927.4 2344.19  4945.0 2340.03
  4956.0 2334.17  4965.0 2332.48  4979.1 2329.74  4986.7 2327.30  4987.0 2326.80
  4991.2 2327.30  4996.6 2329.10  5004.4 2329.10  5030.2 2334.07  5083.5 2334.65
  5131.0 2337.58  5151.2 2340.39  5157.6 2343.53  5162.6 2344.02  5169.0 2347.23
  5221.8 2367.26  5231.7 2369.83  5236.7 2368.39  5272.2 2375.14  5302.5 2379.08
  5310.8 2381.21  5315.8 2380.18  5322.6 2383.89  5332.7 2386.89  5352.9 2391.08
#Mann=5,-1,0
  4890.1    0.07       0  4965.0    0.16       0  4986.7    0.07       0
  4991.2    0.16       0  5169.0    0.07       0
Bank Sta=4986.7,4991.2
Exp/Cntr=0.3,0.1

Type RM Length L Ch R = 1,2891,495,495,495
BEGIN DESCRIPTION:
Bitter Creek Trib8T1 5.0
END DESCRIPTION:
XS GIS Cut Line= 3
      1431005.01      6835387.99      1430624.88      6835808.28
      1430805.01      6836188.03
#Sta/Elev= 30
  4433.3 2363.49  4436.7 2363.49  4465.8 2352.10  4483.0 2346.62  4503.9 2343.09
  4595.9 2333.82  4660.1 2329.85  4794.6 2327.03  4935.8 2328.28  4964.2 2325.87
  4985.9 2326.91  5019.6 2322.98  5019.9 2322.48  5024.1 2322.98  5031.3 2325.98
  5036.8 2325.47  5054.0 2329.63  5165.7 2332.75  5201.5 2335.19  5240.7 2342.25
  5264.2 2347.08  5269.7 2346.59  5286.9 2352.05  5292.5 2350.86  5309.6 2357.05
  5315.2 2362.46  5320.7 2360.44  5353.9 2375.77  5376.0 2378.37  5420.3 2389.18
#Mann=5,-1,0
  4433.3    0.07       0  4465.8    0.16       0  5019.6    0.07       0
  5024.1    0.16       0  5240.7    0.07       0
Bank Sta=5019.6,5024.1
Exp/Cntr=0.3,0.1

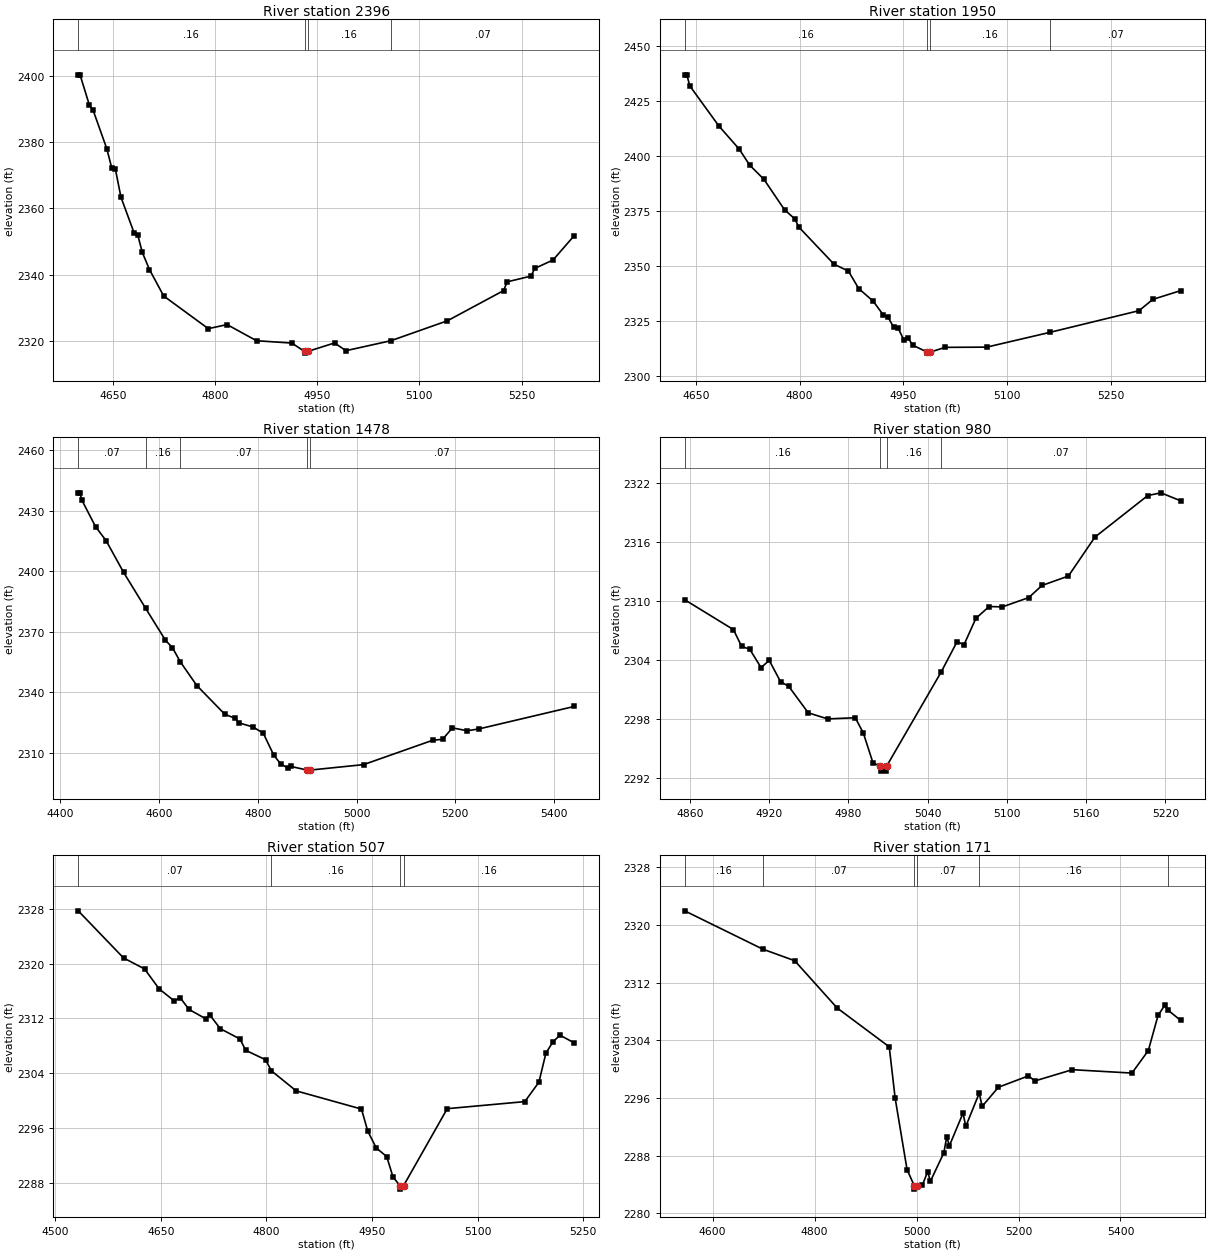
Type RM Length L Ch R = 1,2396,446,446,446
BEGIN DESCRIPTION:
Bitter Creek Trib8T1 4.0
END DESCRIPTION:
XS GIS Cut Line= 3
      1430405.01      6835087.95      1430287.96      6835471.49
      1430205.00      6835788.00
#Sta/Elev= 30
  4599.0 2400.40  4601.7 2400.40  4615.5 2391.17  4620.7 2389.79  4640.9 2378.10
  4648.3 2372.19  4653.5 2371.95  4661.8 2363.37  4681.1 2352.60  4686.3 2352.06
  4693.1 2346.71  4703.6 2341.53  4724.5 2333.53  4790.0 2323.65  4817.6 2324.88
  4860.8 2320.00  4912.7 2319.29  4931.3 2316.75  4931.6 2316.25  4935.9 2316.75
  4975.4 2319.33  4992.1 2316.99  5058.1 2320.00  5141.1 2326.03  5223.6 2335.16
  5228.8 2337.80  5264.0 2339.55  5269.2 2341.85  5296.2 2344.41  5327.2 2351.75
#Mann=4,-1,0
  4599.0    0.16       0  4931.3    0.07       0  4935.9    0.16       0
  5058.1    0.07       0
Bank Sta=4931.3,4935.9
Exp/Cntr=0.3,0.1

Type RM Length L Ch R = 1,1950,472,472,472
BEGIN DESCRIPTION:
Bitter Creek Trib8T1 3.0
END DESCRIPTION:
XS GIS Cut Line= 3
      1430255.01      6834937.99      1430044.80      6835237.59
      1430055.00      6835588.05
#Sta/Elev= 30
  4634.0 2437.09  4637.1 2437.09  4641.4 2432.06  4683.3 2413.84  4712.9 2403.23
  4727.7 2396.06  4748.6 2389.47  4778.3 2375.63  4792.8 2371.60  4799.2 2367.69
  4849.7 2350.89  4870.6 2347.73  4885.5 2339.75  4906.4 2334.04  4921.2 2327.66
  4927.3 2327.05  4936.0 2322.13  4942.1 2322.00  4950.8 2316.25  4956.9 2317.10
  4963.8 2313.96  4984.2 2310.88  4984.5 2310.38  4989.0 2310.88  5010.4 2313.01
  5070.4 2313.11  5162.2 2319.87  5290.5 2329.71  5310.5 2334.86  5350.6 2338.83
#Mann=4,-1,0
  4634.0    0.16       0  4984.2    0.07       0  4989.0    0.16       0
  5162.2    0.07       0
Bank Sta=4984.2,4989
Exp/Cntr=0.3,0.1

Type RM Length L Ch R = 1,1478,498,498,498
BEGIN DESCRIPTION:
Bitter Creek Trib8T1 2.0
END DESCRIPTION:
XS GIS Cut Line= 3
      1430054.98      6834788.02      1429653.28      6835183.78
      1429647.41      6835624.54
#Sta/Elev= 30
  4436.1 2438.96  4439.6 2438.96  4443.1 2435.51  4471.4 2422.08  4492.6 2415.23
  4528.0 2399.49  4572.7 2381.61  4612.9 2365.74  4627.0 2362.09  4642.6 2355.18
  4676.4 2343.27  4733.0 2329.04  4754.3 2326.97  4761.3 2324.76  4789.6 2322.77
  4810.9 2319.68  4832.0 2308.83  4846.2 2304.37  4860.3 2302.41  4867.4 2303.10
  4900.3 2301.29  4900.6 2300.79  4905.2 2301.29  5014.2 2304.02  5154.2 2316.11
  5174.2 2316.59  5194.2 2322.26  5224.2 2320.84  5247.8 2321.74  5440.8 2332.90
#Mann=5,-1,0
  4436.1    0.07       0  4572.7    0.16       0  4642.6    0.07       0
  4900.3    0.07       0  4905.2    0.07       0
Bank Sta=4900.3,4905.2
Exp/Cntr=0.3,0.1

Type RM Length L Ch R = 1,980,473,473,473
BEGIN DESCRIPTION:
Bitter Creek Trib8T1 1.0
END DESCRIPTION:
XS GIS Cut Line= 3
      1429355.03      6834987.98      1429237.96      6835071.49
      1429245.41      6835302.87
#Sta/Elev= 30
  4856.2 2310.10  4893.1 2307.06  4899.3 2305.35  4905.4 2305.07  4914.0 2303.20
  4920.2 2303.93  4928.8 2301.75  4934.9 2301.30  4949.7 2298.60  4964.4 2297.98
  4985.3 2298.10  4991.4 2296.54  4998.7 2293.51  5004.1 2293.17  5004.4 2292.67
  5008.6 2292.67  5009.0 2293.17  5050.3 2302.75  5062.4 2305.85  5067.5 2305.50
  5076.6 2308.21  5086.6 2309.41  5096.6 2309.37  5116.6 2310.32  5126.6 2311.55
  5146.6 2312.51  5166.6 2316.46  5206.6 2320.69  5216.6 2320.97  5231.5 2320.16
#Mann=4,-1,0
  4856.2    0.16       0  5004.1    0.07       0  5009.0    0.16       0
  5050.3    0.07       0
Bank Sta=5004.1,5009
Exp/Cntr=0.3,0.1

Type RM Length L Ch R = 1,507,336,336,336
BEGIN DESCRIPTION:
Bitter Creek Trib8T1 0.1
END DESCRIPTION:
XS GIS Cut Line= 3
      1429305.00      6834488.00      1428918.63      6834751.21
      1428905.00      6834988.02
#Sta/Elev= 30
  4532.5 2327.70  4596.9 2320.82  4626.7 2319.22  4647.7 2316.28  4668.7 2314.57
  4677.6 2314.99  4689.8 2313.31  4713.5 2311.95  4719.5 2312.49  4734.4 2310.49
  4762.4 2308.98  4770.4 2307.34  4798.7 2305.95  4807.1 2304.33  4842.2 2301.41
  4935.0 2298.75  4943.9 2295.54  4956.0 2293.07  4970.9 2291.81  4979.8 2288.83
  4989.8 2287.56  4990.2 2287.06  4994.8 2287.56  5056.9 2298.81  5167.1 2299.84
  5187.1 2302.67  5197.1 2306.93  5207.1 2308.57  5217.1 2309.54  5237.2 2308.42
#Mann=4,-1,0
  4532.5    0.07       0  4807.1    0.16       0  4989.8    0.07       0
  4994.8    0.16       0
Bank Sta=4989.8,4994.8
Exp/Cntr=0.3,0.1

Type RM Length L Ch R = 1,171,0,0,0
BEGIN DESCRIPTION:
Bitter Creek Trib8T1 4311
END DESCRIPTION:
XS GIS Cut Line= 3
      1428881.35      6834075.00      1428711.74      6834497.10
      1428870.48      6834990.18
#Sta/Elev= 30
  4545.1 2321.98  4698.1 2316.67  4760.9 2315.06  4844.2 2308.50  4946.4 2303.11
  4957.9 2296.03  4981.3 2286.09  4995.3 2283.87  4995.6 2283.37  5000.3 2283.87
  5011.5 2283.94  5021.8 2285.80  5027.1 2284.45  5053.5 2288.41  5059.2 2290.64
  5064.4 2289.39  5091.2 2293.92  5096.5 2292.06  5123.0 2296.69  5128.6 2294.85
  5160.6 2297.51  5219.5 2299.08  5232.1 2298.38  5305.6 2299.94  5422.5 2299.47
  5454.6 2302.59  5473.7 2307.46  5486.6 2308.85  5493.7 2308.17  5518.0 2306.79
#Mann=6,-1,0
  4545.1    0.16       0  4698.1    0.07       0  4995.3    0.07       0
  5000.3    0.07       0  5123.0    0.16       0  5493.7    0.07       0
Bank Sta=4995.3,5000.3
Exp/Cntr=0.3,0.1

Chan Stop Cuts=-1