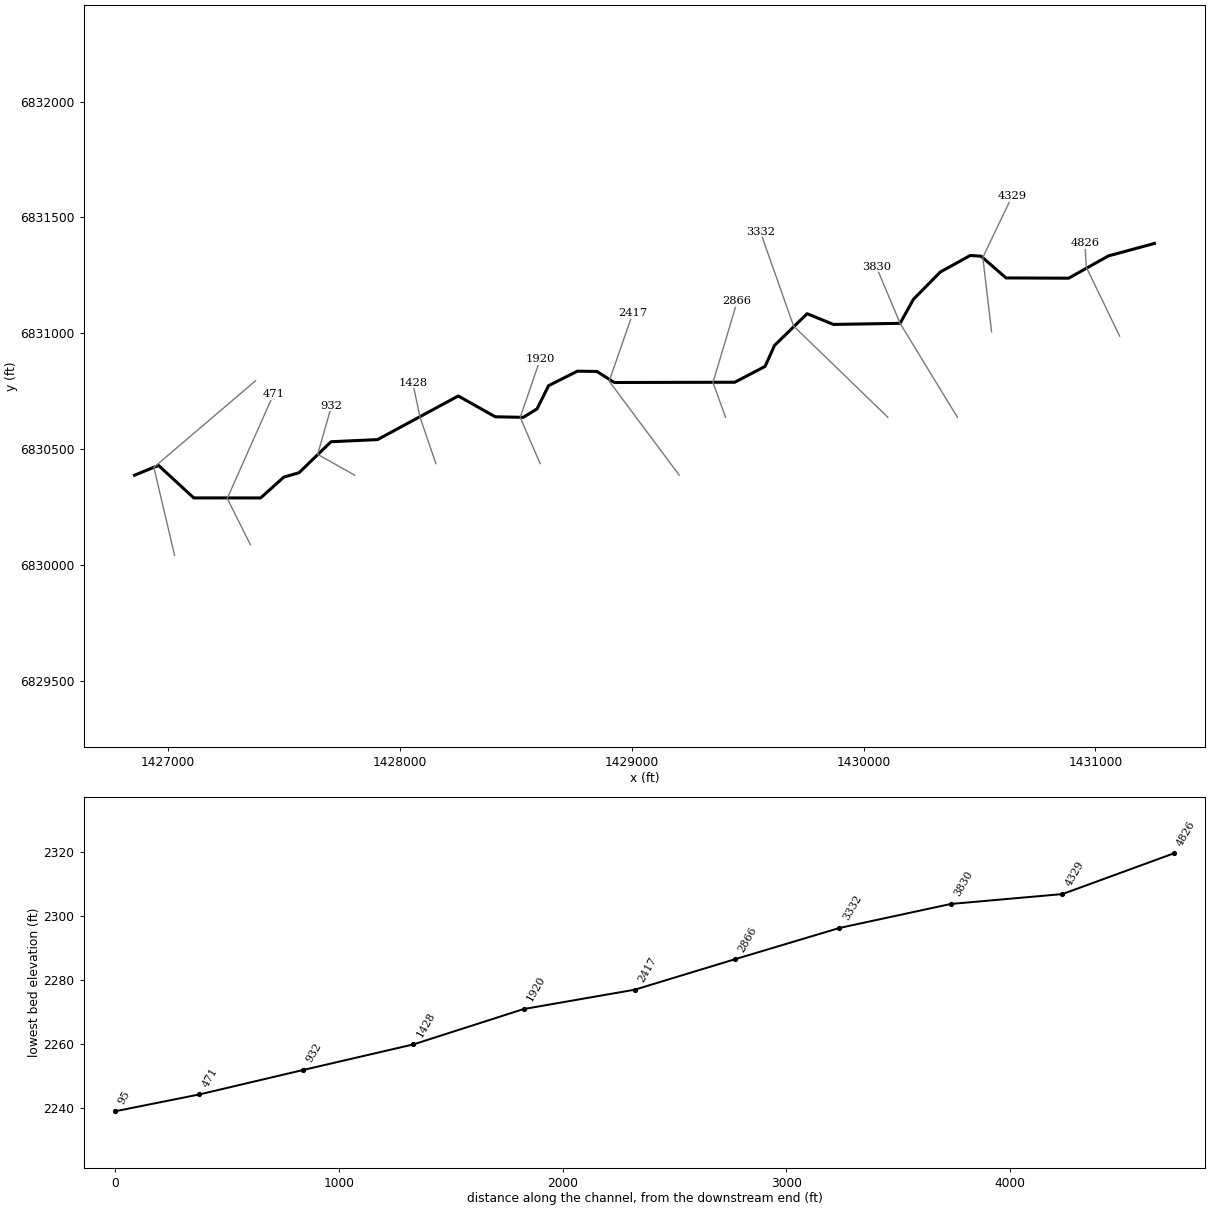
--- Bitter Creek Trib8T2.prj (project) ---

Proj Title=Bitter Creek Trib8T2 Base Level Engineering
Current Plan=p01
Default Exp/Contr=0.3,0.1
English Units
Geom File=g01
Flow File=f01
Plan File=p01
Y Axis Title=Elevation
X Axis Title(PF)=Main Channel Distance
X Axis Title(XS)=Station
BEGIN DESCRIPTION:
Bitter Creek Trib8T2
END DESCRIPTION:
DSS Export Rating Curves= 0
DSS Export Rating Curve Sorted= 0
DSS Export Volume Flow Curves= 0
DXF OffsetX= 0
DXF OffsetY= 0
DXF ScaleX= 1
DXF ScaleY= 10

--- Bitter Creek Trib8T2.p01 (plan) ---

Plan Title=Multiple Run
Short Identifier=Multiple
Geom File=g01
Flow File=f01
Subcritical Flow
K Sum by GR= 0
Std Step Tol= 0.01
Critical Tol= 0.01
Num of Std Step Trials= 20
Max Error Tol= 0.3
Flow Tol Ratio= 0.001
Split Flow NTrial= 30
Split Flow Tol= 0.02
Split Flow Ratio= 0.02
Log Output Level= 0
Friction Slope Method= 1
Unsteady Friction Slope Method= 2
Unsteady Bridges Friction Slope Method= 1
Parabolic Critical Depth
Global Vel Dist=  1 , 1 , 1
Global Log Level= 0
CheckData=True
Encroach Param= -1, 0, 0, 0
BEGIN DESCRIPTION:
Multiple Run
END DESCRIPTION:

--- Bitter Creek Trib8T2.f01 (steady flow) ---

Flow Title=Multiple
Program Version=4.10
Number of Profiles= 7
Profile Names=10-year,25-year,50-year,1pct_min,100-year,1pct_plu,500-year
River Rch & RM=Bitter Creek Tri,Reach-1         ,4826
     380     551     699     442     881    1758    1415
River Rch & RM=Bitter Creek Tri,Reach-1         ,3830
     458     671     857     544    1086    2166    1765
Boundary for River Rch & Prof#=Bitter Creek Tri,Reach-1         , 1
Up Type= 0
Dn Type= 3
Dn Slope=0.013
Boundary for River Rch & Prof#=Bitter Creek Tri,Reach-1         , 2
Up Type= 0
Dn Type= 3
Dn Slope=0.013
Boundary for River Rch & Prof#=Bitter Creek Tri,Reach-1         , 3
Up Type= 0
Dn Type= 3
Dn Slope=0.013
Boundary for River Rch & Prof#=Bitter Creek Tri,Reach-1         , 4
Up Type= 0
Dn Type= 3
Dn Slope=0.013
Boundary for River Rch & Prof#=Bitter Creek Tri,Reach-1         , 5
Up Type= 0
Dn Type= 3
Dn Slope=0.013
Boundary for River Rch & Prof#=Bitter Creek Tri,Reach-1         , 6
Up Type= 0
Dn Type= 3
Dn Slope=0.013
Boundary for River Rch & Prof#=Bitter Creek Tri,Reach-1         , 7
Up Type= 0
Dn Type= 3
Dn Slope=0.013
DSS Import GetInterval= 0
DSS Import GetPeak= 0
DSS Import FillOption= 0

--- Bitter Creek Trib8T2.g01 (geometry) ---

Geom Title=Existing Conditions
Program Version=4.10

River Reach=Bitter Creek Tri,Reach-1
Reach XY= 30
        1431255.        6831388.      1431056.58      6831334.18
      1430884.97      6831238.06      1430614.59      6831239.21
      1430507.29       6831332.9      1430460.72      6831336.12
      1430331.53      6831264.99      1430215.79      6831147.66
       1430157.7      6831043.36      1429870.21      6831038.54
      1429756.63      6831084.87      1429615.79      6830947.66
      1429575.47      6830857.62       1429444.5       6830789.2
      1428925.03      6830788.07      1428849.43      6830835.71
      1428765.54      6830836.92      1428641.44      6830774.52
      1428591.54      6830674.38      1428532.44      6830637.74
      1428410.93      6830640.23      1428251.69      6830729.98
      1427903.45      6830541.75      1427702.55      6830532.54
      1427564.68      6830398.78      1427498.96      6830379.82
      1427399.14      6830290.06      1427110.44      6830290.17
      1426958.39      6830430.41        1426855.        6830388.

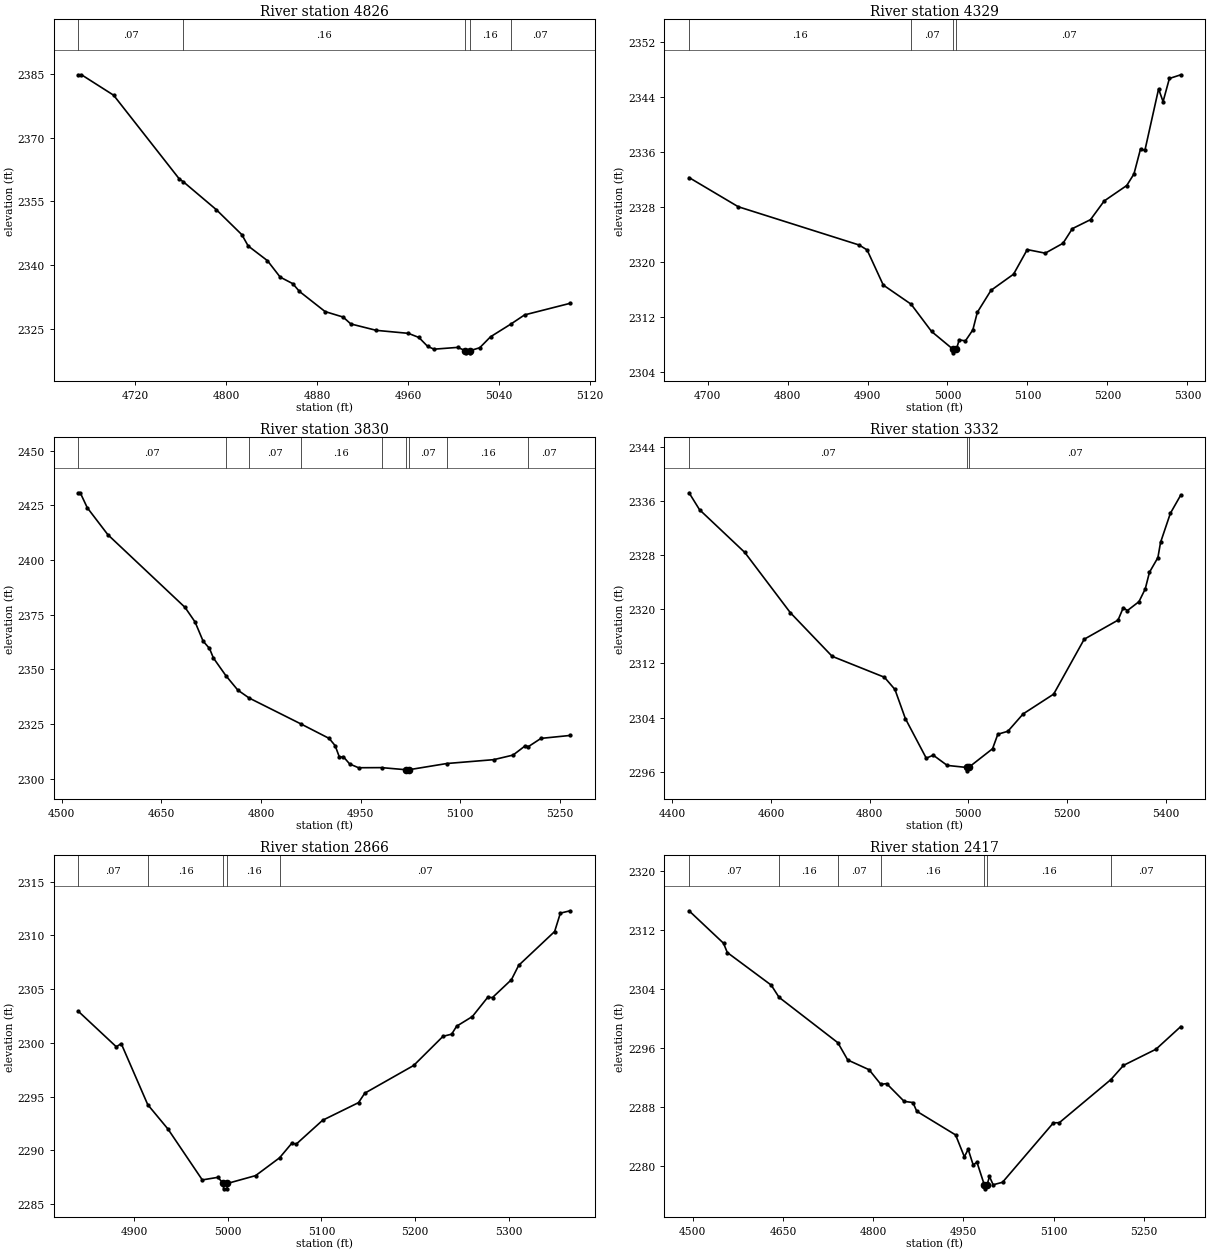
Type RM Length L Ch R = 1 ,4826    ,497,497,497
BEGIN DESCRIPTION:
Bitter Creek Trib8T2 9.0
END DESCRIPTION:
XS GIS Cut Line= 3
      1431105.01      6830987.99      1430961.12       6831285.3
        1430955.      6831388.02
#Sta/Elev= 30
  4669.7 2384.75  4672.5 2384.75  4700.8 2379.95  4758.6  2360.3  4762.2 2359.62
  4791.2 2353.08  4813.8 2347.18  4819.3 2344.55  4836.3 2341.09  4847.5 2337.23
  4858.6 2335.69  4864.5 2333.86  4887.1 2329.13    4903 2327.84  4909.7 2326.23
  4932.2 2324.72  4960.4 2324.02  4969.7 2323.05  4977.4 2320.96    4983  2320.3
  5003.9 2320.72  5010.7 2319.94    5011 2319.44  5014.5 2319.44  5014.7 2319.94
  5023.3 2320.64  5032.8 2323.21  5050.5 2326.16  5062.8 2328.35  5102.9 2331.07
#Mann= 5 ,-1 , 0
  4669.7     .07       0  4762.2     .16       0  5010.7     .07       0
  5014.7     .16       0  5050.5     .07       0
Bank Sta=5010.7,5014.7
XS Rating Curve= 0 ,0
Exp/Cntr=0.3,0.1

Type RM Length L Ch R = 1 ,4329    ,499,499,499
BEGIN DESCRIPTION:
Bitter Creek Trib8T2 8.0
END DESCRIPTION:
XS GIS Cut Line= 3
      1430552.41       6831006.9      1430514.67      6831327.79
      1430640.61       6831590.9
#Sta/Elev= 30
  4676.9 2332.26  4738.4 2328.01  4889.5 2322.44  4899.5 2321.72  4919.7 2316.61
  4954.5 2313.82  4980.1 2309.85  5007.1 2307.24  5007.3 2306.74  5011.1 2307.24
  5014.6 2308.63  5022.4 2308.48  5031.7 2310.08  5037.3 2312.64  5054.4 2315.84
  5082.6 2318.19  5099.7 2321.77  5122.2 2321.25  5144.4 2322.69  5156.1 2324.82
  5178.8 2326.13  5195.9 2328.85  5224.1  2331.1  5233.1 2332.78  5241.3 2336.42
  5246.8 2336.22  5263.9 2345.16  5269.5 2343.31  5277.4 2346.68  5291.7 2347.22
#Mann= 4 ,-1 , 0
  4676.9     .16       0  4954.5     .07       0  5007.1     .07       0
  5011.1     .07       0
Bank Sta=5007.1,5011.1
XS Rating Curve= 0 ,0
Exp/Cntr=0.3,0.1

Type RM Length L Ch R = 1 ,3830    ,498,498,498
BEGIN DESCRIPTION:
Bitter Creek Trib8T2 7.0
END DESCRIPTION:
XS GIS Cut Line= 3
      1430404.98      6830638.03       1430157.7      6831043.36
      1430055.01      6831287.98
#Sta/Elev= 30
  4525.2 2430.79  4528.1 2430.79  4538.7 2423.94  4569.7 2411.61  4685.8 2378.39
  4700.9 2371.71    4713 2362.96  4722.6 2359.61  4728.5 2355.25  4747.3 2347.15
  4765.2 2340.58  4782.2 2336.96  4860.1 2325.11  4902.7 2318.47  4911.7 2315.17
  4918.2 2309.83    4924 2310.13  4933.6 2306.78  4946.9 2305.07  4981.6 2305.12
  5018.5 2304.15  5018.8 2303.65  5022.6 2304.15  5079.8    2307  5150.3 2308.76
  5179.4 2310.85  5197.8  2315.1  5202.6 2314.74  5221.5 2318.49  5265.3 2319.83
#Mann= 9 ,-1 , 0
  4525.2     .07       0  4747.3     .16       0  4782.2     .07       0
  4860.1     .16       0  4981.6     .07       0  5018.5     .07       0
  5022.6     .07       0  5079.8     .16       0  5202.6     .07       0
Bank Sta=5018.5,5022.6
XS Rating Curve= 0 ,0
Exp/Cntr=0.3,0.1

Type RM Length L Ch R = 1 ,3332    ,466,466,466
BEGIN DESCRIPTION:
Bitter Creek Trib8T2 6.0
END DESCRIPTION:
XS GIS Cut Line= 3
      1430105.03      6830637.97      1429698.25      6831031.54
      1429554.99      6831438.03
#Sta/Elev= 30
    4434 2337.18  4455.3 2334.68  4547.1 2328.37  4639.2  2319.5  4724.1 2313.05
  4830.1 2309.96  4851.4 2308.16  4872.5 2303.87  4914.9 2298.02  4929.1 2298.46
  4957.4 2296.95  4996.7 2296.65    4997 2296.15  5000.8 2296.65  5049.3 2299.41
    5060 2301.55  5080.4 2301.99  5111.3 2304.55  5173.2 2307.47  5235.1 2315.57
  5303.7 2318.39  5314.3 2320.22  5322.7  2319.8  5346.1 2321.11  5358.9    2323
  5367.4 2325.45  5384.5 2327.61  5389.9 2329.86  5409.8 2334.15    5431 2336.86
#Mann= 3 ,-1 , 0
    4434     .07       0  4996.7     .07       0  5000.8     .07       0
Bank Sta=4996.7,5000.8
XS Rating Curve= 0 ,0
Exp/Cntr=0.3,0.1

Type RM Length L Ch R = 1 ,2866    ,449,449,449
BEGIN DESCRIPTION:
Bitter Creek Trib8T2 5.0
END DESCRIPTION:
XS GIS Cut Line= 3
      1429404.99      6830638.04      1429350.48      6830787.94
      1429454.99      6831137.97
#Sta/Elev= 30
  4840.5 2302.93    4881 2299.63  4886.3 2299.92  4914.6 2294.24  4936.2 2291.97
  4972.8 2287.24  4989.4 2287.48  4995.3 2286.91  4995.5 2286.41  4999.2 2286.41
  4999.5 2286.91  5029.7 2287.64  5055.3  2289.3  5068.1 2290.63  5073.3 2290.59
  5101.2 2292.79  5139.5 2294.43  5146.2 2295.31  5198.4 2297.89  5229.7  2300.6
  5238.9  2300.8  5244.2 2301.54    5261 2302.44  5277.3 2304.22  5282.5 2304.21
  5302.7 2305.87  5310.4  2307.2  5348.8 2310.35  5354.9 2312.06  5365.3 2312.28
#Mann= 5 ,-1 , 0
  4840.5     .07       0  4914.6     .16       0  4995.3     .07       0
  4999.5     .16       0  5055.3     .07       0
Bank Sta=4995.3,4999.5
XS Rating Curve= 0 ,0
Exp/Cntr=0.3,0.1

Type RM Length L Ch R = 1 ,2417    ,497,497,497
BEGIN DESCRIPTION:
Bitter Creek Trib8T2 4.0
END DESCRIPTION:
XS GIS Cut Line= 3
        1429205.        6830388.      1428902.66      6830793.75
      1429004.99      6831087.96
#Sta/Elev= 30
    4494 2314.57  4551.3 2310.17  4557.6 2308.91  4630.6 2304.49  4643.6 2302.84
  4741.4 2296.68  4757.8 2294.34  4793.3 2293.02  4812.9 2291.03  4822.4 2291.14
  4851.6 2288.73  4866.2 2288.57  4872.5 2287.39  4937.1 2284.18  4951.7 2281.21
    4958 2282.23  4966.3 2280.12  4972.6 2280.48    4985 2277.37  4985.3 2276.87
  4989.3 2277.37  4993.4 2278.55  4999.5 2277.42  5015.1 2277.76  5099.8 2285.83
  5109.4 2285.83  5195.3 2291.69  5216.2 2293.61  5270.2  2295.8  5311.5 2298.88
#Mann= 7 ,-1 , 0
    4494     .07       0  4643.6     .16       0  4741.4     .07       0
  4812.9     .16       0    4985     .07       0  4989.3     .16       0
  5195.3     .07       0
Bank Sta=4985,4989.3
XS Rating Curve= 0 ,0
Exp/Cntr=0.3,0.1

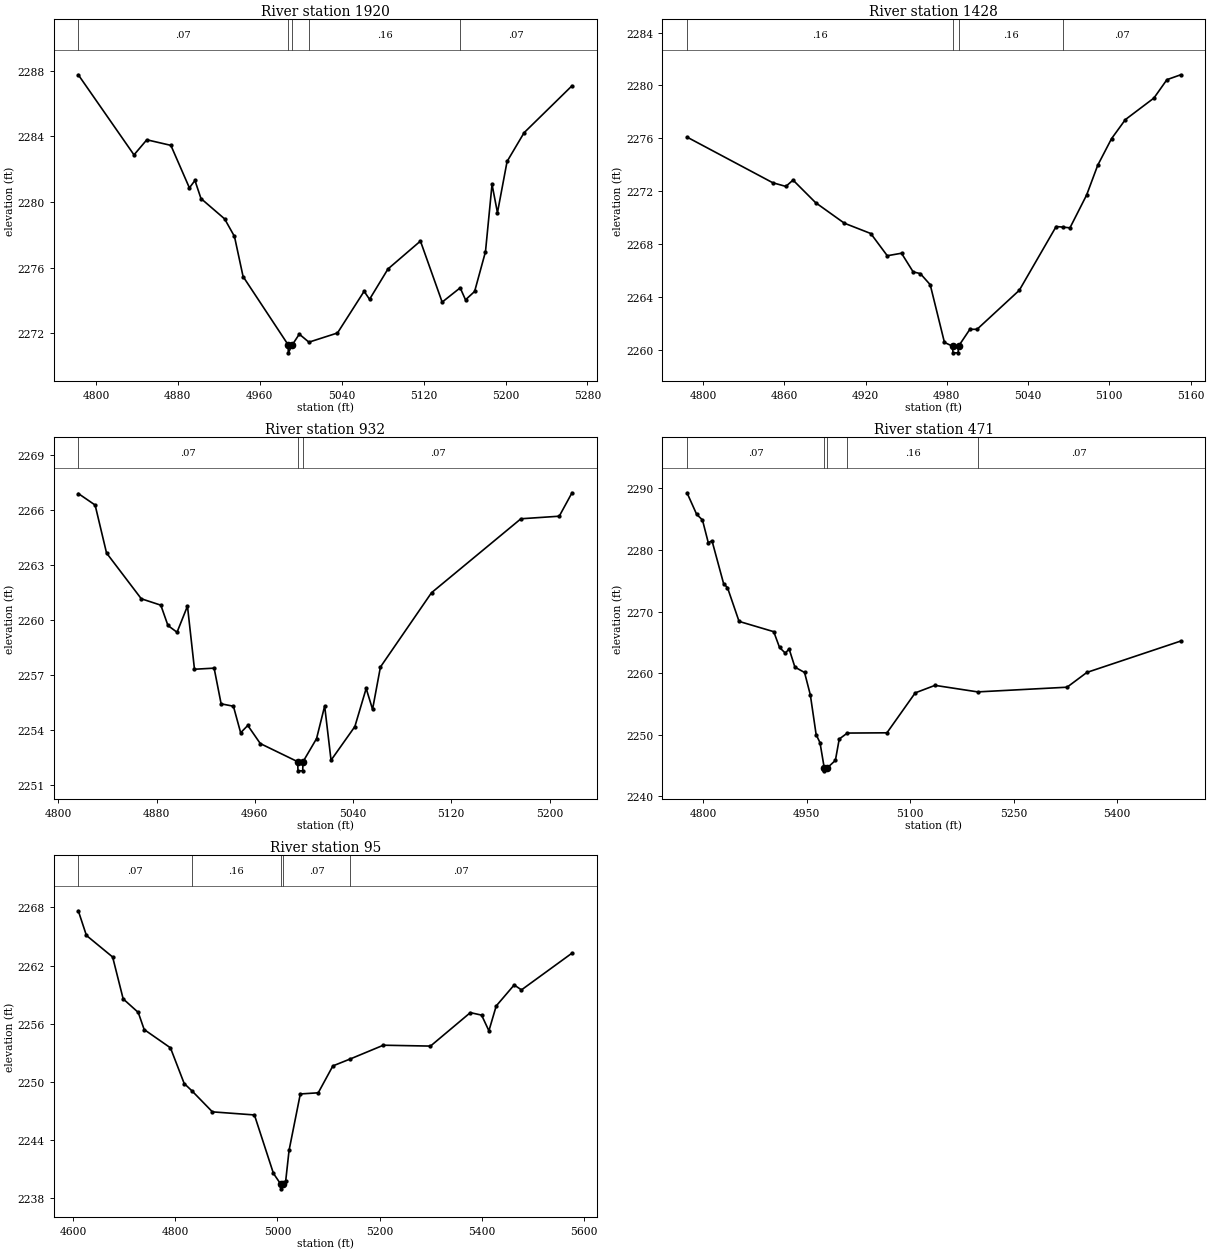
Type RM Length L Ch R = 1 ,1920    ,492,492,492
BEGIN DESCRIPTION:
Bitter Creek Trib8T2 3.0
END DESCRIPTION:
XS GIS Cut Line= 3
      1428604.98      6830438.04      1428518.88      6830637.44
      1428604.98      6830887.95
#Sta/Elev= 30
  4782.8 2287.76  4837.2 2282.88  4849.7  2283.8  4873.2 2283.46  4891.3 2280.87
  4896.7 2281.32  4902.6 2280.22  4925.7 2278.98  4935.3 2277.91  4943.7 2275.47
  4987.6 2271.32  4987.9 2270.82  4991.9 2271.32  4998.6 2271.96    5008 2271.47
  5035.9 2272.03  5061.9 2274.57  5067.2 2274.08  5085.2 2275.93  5116.9 2277.63
  5138.1 2273.91  5155.7 2274.78  5160.9 2274.05  5169.8 2274.56  5180.4 2276.98
  5186.8 2281.08  5192.1 2279.36  5201.5 2282.48  5218.1 2284.23  5264.9 2287.09
#Mann= 5 ,-1 , 0
  4782.8     .07       0  4987.6     .07       0  4991.9     .07       0
    5008     .16       0  5155.7     .07       0
Bank Sta=4987.6,4991.9
XS Rating Curve= 0 ,0
Exp/Cntr=0.3,0.1

Type RM Length L Ch R = 1 ,1428    ,496,496,496
BEGIN DESCRIPTION:
Bitter Creek Trib8T2 2.0
END DESCRIPTION:
XS GIS Cut Line= 3
      1428154.98      6830438.05      1428086.57       6830638.6
        1428055.        6830788.
#Sta/Elev= 30
  4788.1  2276.1  4851.4 2272.65  4861.1 2272.37  4866.4 2272.85  4883.1 2271.14
  4904.3 2269.59  4923.8 2268.81    4936 2267.13  4946.5 2267.32  4955.1 2265.91
  4960.4 2265.78  4967.7 2264.94  4978.2 2260.58  4984.2 2260.29  4984.5 2259.79
  4988.3 2259.79  4988.6 2260.29    4997 2261.57  5002.3 2261.57  5033.5 2264.52
  5060.7 2269.34  5066.1 2269.29  5070.9 2269.24  5083.2 2271.72  5091.4 2273.97
  5101.6 2275.98  5111.8 2277.42  5132.9 2279.05  5142.5 2280.44  5152.7 2280.81
#Mann= 4 ,-1 , 0
  4788.1     .16       0  4984.2     .07       0  4988.6     .16       0
  5066.1     .07       0
Bank Sta=4984.2,4988.6
XS Rating Curve= 0 ,0
Exp/Cntr=0.3,0.1

Type RM Length L Ch R = 1 ,932     ,461,461,461
BEGIN DESCRIPTION:
Bitter Creek Trib8T2 1.0
END DESCRIPTION:
XS GIS Cut Line= 3
      1427805.02      6830387.99      1427644.95      6830478.12
        1427705.        6830688.
#Sta/Elev= 30
  4816.3  2266.9    4830 2266.27  4839.3 2263.65  4867.6 2261.15  4883.5  2260.8
  4889.3 2259.69  4896.7 2259.32  4905.2 2260.75  4910.9  2257.3  4926.9 2257.36
  4932.6 2255.41  4942.6 2255.28  4948.5 2253.83  4954.3 2254.23  4964.5 2253.24
  4994.9 2252.25  4995.2 2251.75    4999 2251.75  4999.3 2252.25  5010.3 2253.51
  5016.9 2255.29  5022.1 2252.33  5041.5 2254.17  5050.7 2256.25  5055.9 2255.11
  5062.3 2257.42  5103.9 2261.48  5176.7 2265.52  5207.9 2265.66  5218.3 2266.94
#Mann= 3 ,-1 , 0
  4816.3     .07       0  4994.9     .07       0  4999.3     .07       0
Bank Sta=4994.9,4999.3
XS Rating Curve= 0 ,0
Exp/Cntr=0.3,0.1

Type RM Length L Ch R = 1 ,471     ,376,376,376
BEGIN DESCRIPTION:
Bitter Creek Trib8T2 0.1
END DESCRIPTION:
XS GIS Cut Line= 3
        1427355.      6830087.99        1427255.      6830287.98
      1427455.02      6830738.04
#Sta/Elev= 30
  4776.4 2289.28  4790.4 2285.78  4798.8 2284.87  4807.2  2281.2  4812.7 2281.47
  4829.5 2274.53  4835.1 2273.89  4851.9 2268.41  4902.2 2266.74  4910.6 2264.18
    4919 2263.26  4924.5 2263.94  4932.9 2260.99  4946.9 2260.12  4955.3 2256.47
  4963.7 2250.03  4969.3 2248.73  4975.4 2244.66  4975.7 2244.16    4980 2244.66
  4991.6 2245.85  4997.2 2249.32  5008.9 2250.29  5066.4 2250.33  5107.4 2256.81
  5136.1 2258.03    5198 2256.97  5327.6 2257.73  5356.4 2260.13  5492.5 2265.22
#Mann= 5 ,-1 , 0
  4776.4     .07       0  4975.4     .07       0    4980     .07       0
  5008.9     .16       0    5198     .07       0
Bank Sta=4975.4,4980
XS Rating Curve= 0 ,0
Exp/Cntr=0.3,0.1

Type RM Length L Ch R = 1 ,95      ,0,0,0
BEGIN DESCRIPTION:
Bitter Creek Trib8T2 4312
END DESCRIPTION:
XS GIS Cut Line= 3
      1427027.76      6830042.54      1426938.46      6830421.87
      1427377.14      6830795.61
#Sta/Elev= 30
  4610.3 2267.66  4626.2 2265.11  4677.5 2262.88  4698.1 2258.55  4727.6 2257.15
  4739.2 2255.38  4790.6 2253.49  4817.5  2249.8  4832.7 2249.04  4872.7 2246.87
  4954.9 2246.55  4992.1 2240.51  5006.2 2239.41  5006.6 2238.91  5010.9 2239.41
  5016.2 2239.77  5022.7 2242.89  5044.7 2248.72  5079.8 2248.84  5108.4 2251.62
  5142.5 2252.34  5207.2 2253.76  5299.4 2253.67  5377.4 2257.13  5399.4 2256.87
  5413.7 2255.25    5428 2257.82  5463.1 2259.99  5477.4 2259.48  5576.3 2263.28
#Mann= 5 ,-1 , 0
  4610.3     .07       0  4832.7     .16       0  5006.2     .07       0
  5010.9     .07       0  5142.5     .07       0
Bank Sta=5006.2,5010.9
XS Rating Curve= 0 ,0
Exp/Cntr=0.3,0.1

Chan Stop Cuts=-1
Use User Specified Reach Order=0
Composite Channel Slope=5