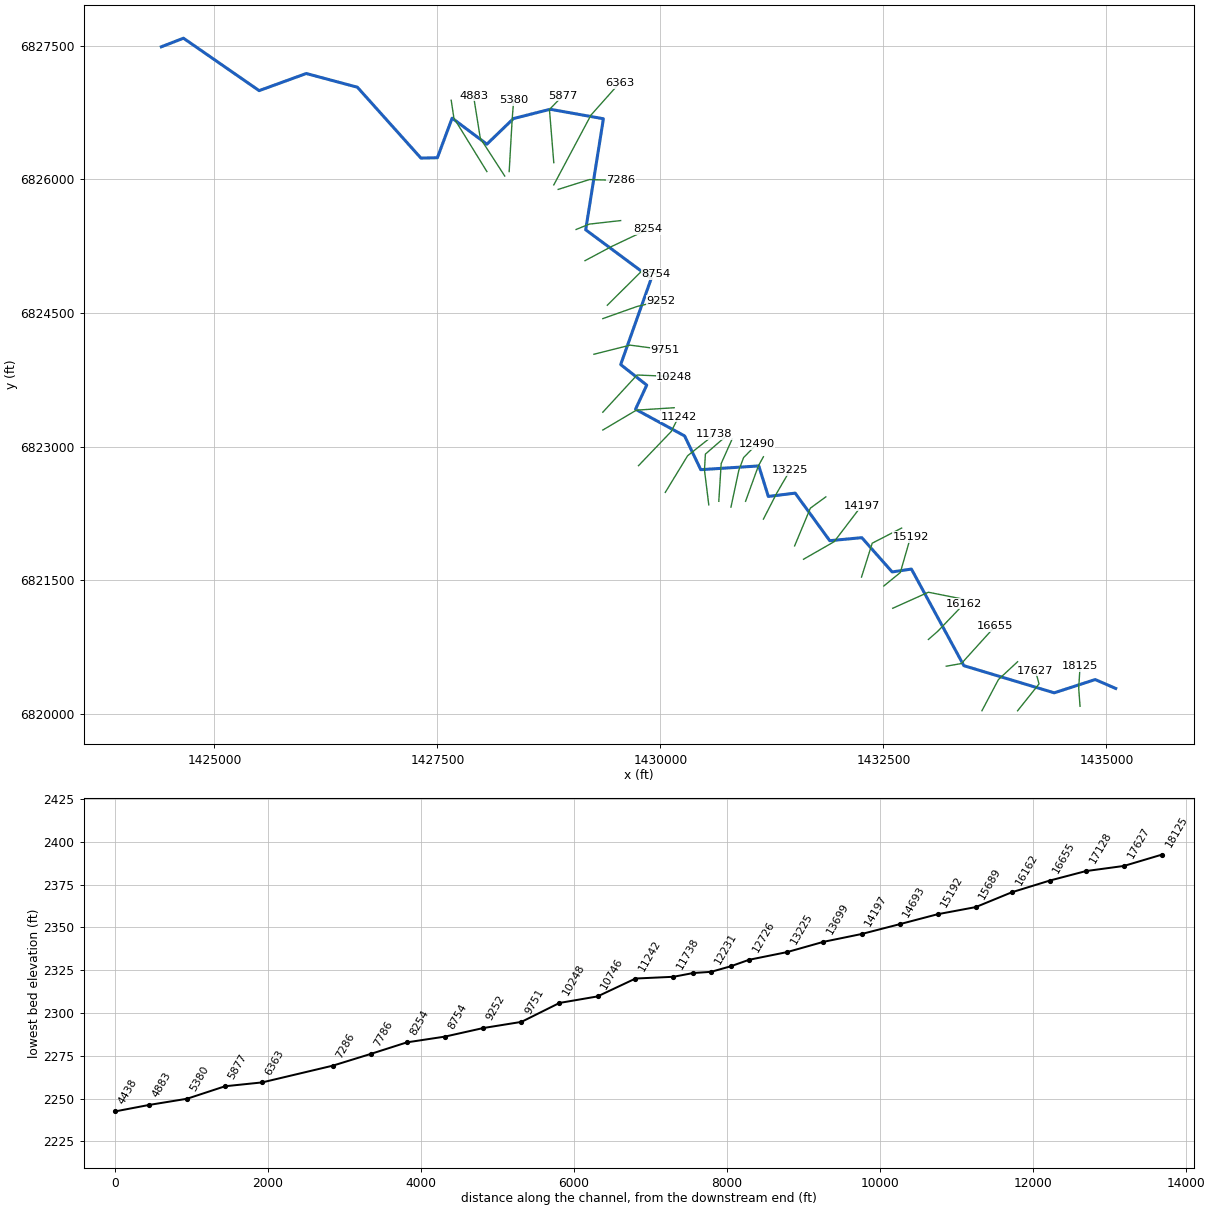
--- Bitter Creek Trib8T3.prj (project) ---

Proj Title=Bitter Creek Trib8T3 Base Level Engineering
Current Plan=p01
Default Exp/Contr=0.3,0.1
English Units
Geom File=g01
Flow File=f01
Plan File=p01
Y Axis Title=Elevation
X Axis Title(PF)=Main Channel Distance
X Axis Title(XS)=Station
BEGIN DESCRIPTION:
Bitter Creek Trib8T3
END DESCRIPTION:
DSS File=dss
DSS Export Rating Curves= 0
DSS Export Rating Curve Sorted= 0
DSS Export Volume Flow Curves= 0
DXF OffsetX= 0
DXF OffsetY= 0
DXF ScaleX= 1
DXF ScaleY= 10

--- Bitter Creek Trib8T3.p01 (plan) ---

Plan Title=Multiple Run
Program Version=4.10
Short Identifier=Multiple Run
Geom File=g01
Flow File=f01
Subcritical Flow
K Sum by GR= 0
Std Step Tol= 0.01
Critical Tol= 0.01
Num of Std Step Trials= 20
Max Error Tol= 0.3
Flow Tol Ratio= 0.001
Split Flow NTrial= 30
Split Flow Tol= 0.02
Split Flow Ratio= 0.02
Log Output Level= 0
Friction Slope Method= 1
Unsteady Friction Slope Method= 2
Unsteady Bridges Friction Slope Method= 1
Parabolic Critical Depth
Global Vel Dist= 1 , 1 , 1
Global Log Level= 0
CheckData=True
Encroach Param=-1 ,0,0, 0
BEGIN DESCRIPTION:
Multiple Run
END DESCRIPTION:
Computation Interval=1HOUR
Output Interval=1HOUR
Run HTab= 0
Run UNet= 0
Run PostProcess= 0
Run WQNet= 0
UNET Theta= 1
UNET Theta Warmup= 1
UNET ZTol= 0.02
UNET ZSATol= 0.05
UNET MxIter= 20
UNET MaxInSteps= 0
UNET DtIC= 0
UNET DtMin= 0
UNET MaxCRTS= 20
UNET WFStab= 2
UNET SFStab= 1
UNET WFX= 1
UNET SFX= 1
UNET DSS MLevel= 4
UNET DZMax Abort= 100
UNET Convert EG Bridges= 0
UNET Use Existing IB Tables=-1
UNET Froude Reduction=False
UNET Froude Limit= 1
UNET Froude Power= 10
UNET Time Slicing=0,0, 5
UNET Junction Losses=0
Instantaneous Interval=1HOUR
DSS File=dss
Write IC File= 0
Write IC File at Sim End=0
Echo Input=False
Echo Parameters=False
Echo Output=False
Write Detailed= 0
WQ AD Non Conservative
WQ ULTIMATE=-1
WQ Max Comp Step=1HOUR
WQ Output Interval=15MIN
WQ Output Selected Increments= 0
WQ Output face flow=0
WQ Output face velocity=0
WQ Output face area=0
WQ Output face dispersion=0
WQ Output cell volume=0
WQ Output cell surface area=0
WQ Output cell continuity=0
WQ Output cumulative cell continuity=0
WQ Output face conc=0
WQ Output face dconc_dx=0
WQ Output face courant=0
WQ Output face peclet=0
WQ Output face adv mass=0
WQ Output face disp mass=0
WQ Output cell mass=0
WQ Output cell source sink temp=0
WQ Output cell source sink nsm=0
WQ Output MaxMinRange=-1
WQ Daily Max Min Mean=-1
WQ Daily Range=0
WQ Daily Time=0
WQ Create Restart=0
WQ Fixed Restart=0
WQ System Summary=0
WQ Use Fixed Temperature=0
Sorting and Armoring Iterations= 10
XS Update Threshold= 0.02
Hydraulics Update Threshold= 0.02
Energy Slope Method= 1
Volume Change Method= 0
XS Weighting Method= 0
Number of US Weighted Cross Sections= 1
Number of DS Weighted Cross Sections= 1
Upstream XS Weight=0.25
Main XS Weight=0.5
Downstream XS Weight=0.25
Number of DS XS's Weighted with US Boundary= 1
Upstream Boundary Weight= 1
Weight of XSs Associated with US Boundary= 0
Number of US XS's Weighted with DS Boundary= 1
Downstream Boundary Weight= 0.5
Weight of XSs Associated with DS Boundary= 0.5
Sediment Output Level= 4
Mass or Volume Output= 0
Output Increment Type= 1
Profile and TS Output Increment= 10
XS Output Flag= 0
XS Output Increment= 10
Disregard all LS=0
Disregard all Conn=0
Disregard all Breaches=0
Disregard all Pumps=0

--- Bitter Creek Trib8T3.f01 (steady flow) ---

Flow Title=Multiple
Number of Profiles=7
Profile Names=10-year,25-year,50-year,1pct_min,100-year,1pct_plu,500-year
River Rch & RM= Bitter Creek Tri,Reach-1,18125
     375     539     679     426     850    1696    1347
River Rch & RM= Bitter Creek Tri,Reach-1,17128
     566     831    1062     674    1345    2684    2185
River Rch & RM= Bitter Creek Tri,Reach-1,10248
     632     932    1195     761    1518    3029    2482
River Rch & RM= Bitter Creek Tri,Reach-1,6363
    1133    1718    2243    1452    2898    5782    4899
Boundary for River Rch & Prof#=Bitter Creek Tri,Reach-1,1
Up Type=0
Dn Type=3
Dn Slope=0.005
Boundary for River Rch & Prof#=Bitter Creek Tri,Reach-1,2
Up Type=0
Dn Type=3
Dn Slope=0.005
Boundary for River Rch & Prof#=Bitter Creek Tri,Reach-1,3
Up Type=0
Dn Type=3
Dn Slope=0.005
Boundary for River Rch & Prof#=Bitter Creek Tri,Reach-1,4
Up Type=0
Dn Type=3
Dn Slope=0.005
Boundary for River Rch & Prof#=Bitter Creek Tri,Reach-1,5
Up Type=0
Dn Type=3
Dn Slope=0.005
Boundary for River Rch & Prof#=Bitter Creek Tri,Reach-1,6
Up Type=0
Dn Type=3
Dn Slope=0.005
Boundary for River Rch & Prof#=Bitter Creek Tri,Reach-1,7
Up Type=0
Dn Type=3
Dn Slope=0.005

--- Bitter Creek Trib8T3.g01 (geometry) ---

Geom Title=Existing Conditions
Program Version=4.10

River Reach=Bitter Creek Tri,Reach-1
Reach XY= 30
        1435105.        6820288.      1434874.99      6820388.06
      1434415.44      6820239.05      1433402.42      6820543.71
      1432814.71      6821627.82      1432598.54      6821595.64
      1432258.23      6821980.16      1431898.92      6821946.13
      1431511.05      6822479.88      1431210.18      6822442.59
      1431103.61      6822784.97      1430452.71      6822743.06
      1430271.76      6823121.54      1429721.13      6823420.98
      1429847.23      6823691.41      1429554.99      6823922.53
      1429897.72       6824888.1      1429162.79      6825434.58
      1429361.32       6826680.5      1428765.43      6826786.95
      1428352.57       6826682.6      1428054.99      6826395.07
      1427665.43      6826687.19      1427499.92      6826243.03
      1427315.44      6826239.05      1426603.42      6827034.18
      1426029.92       6827188.2      1425501.69      6826996.02
      1424653.44      6827584.26        1424405.        6827488.

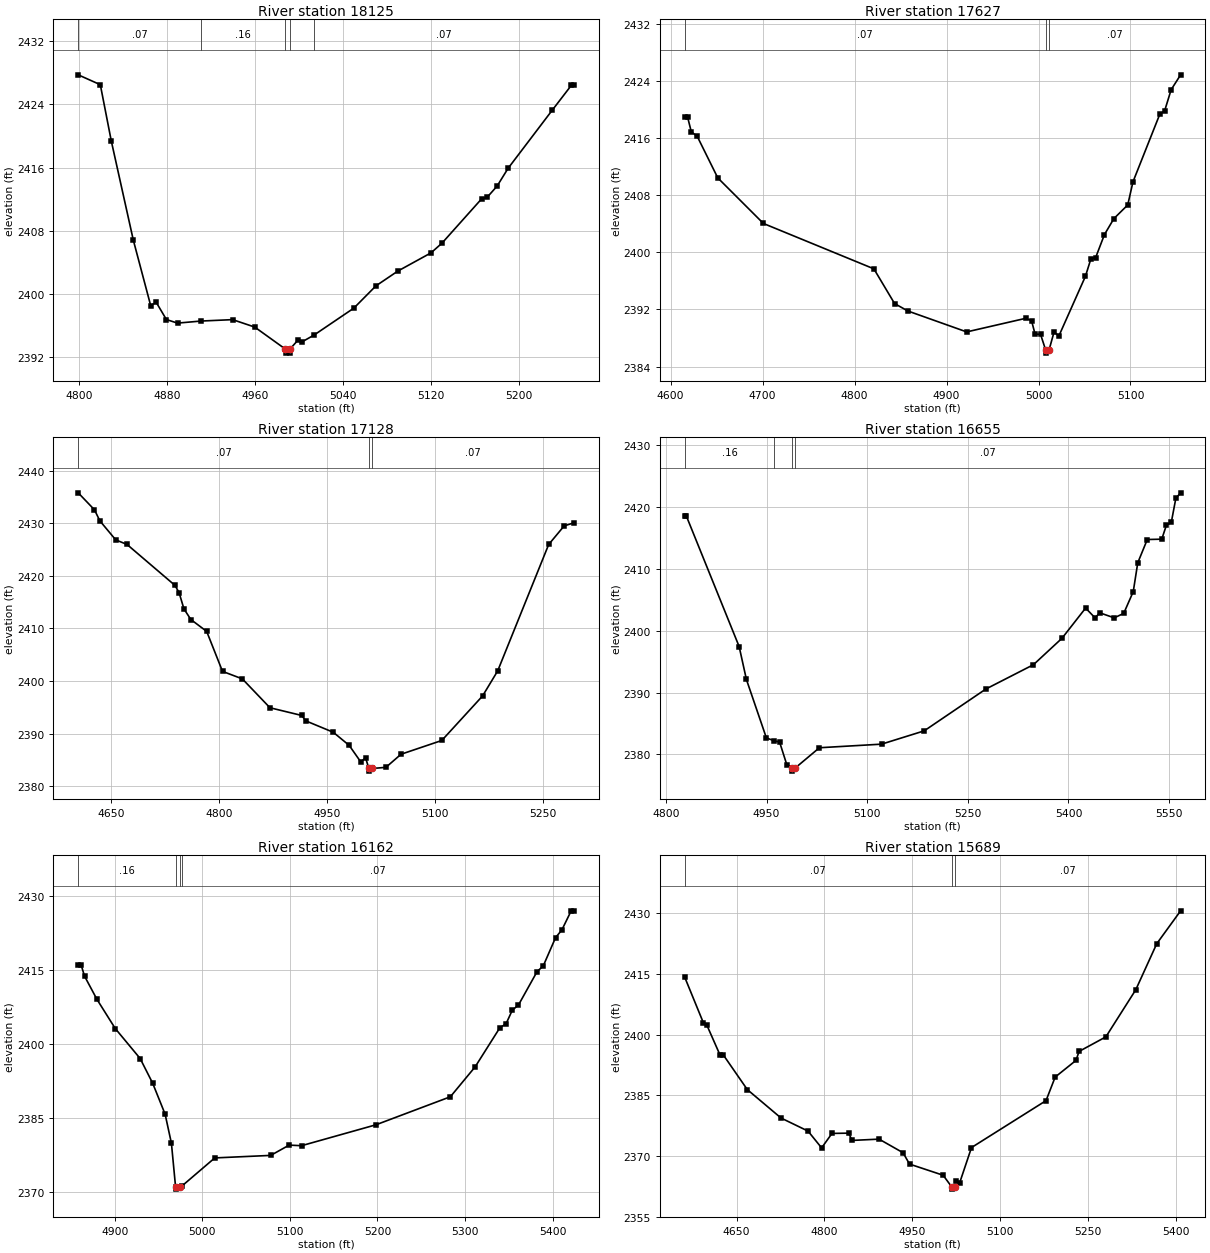
Type RM Length L Ch R = 1 ,18125   ,498,498,498
BEGIN DESCRIPTION:
Bitter Creek Trib8T3 34.0
END DESCRIPTION:
XS GIS Cut Line= 3
        1434705.        6820088.      1434689.94      6820288.13
        1434705.      6820537.98
#Sta/Elev= 30
  4799.3 2427.74  4819.4 2426.49  4829.4 2419.35  4849.4 2406.82  4865.2 2398.53
  4870.2 2398.95  4879.5 2396.76  4889.6 2396.31  4910.9 2396.57  4939.7 2396.75
  4959.8 2395.81  4987.8 2393.01  4988.1 2392.51  4991.6 2392.51  4991.8 2393.01
  4999.6 2394.23  5002.9 2393.94  5013.8  2394.8    5050 2398.21    5070 2401.02
    5090  2402.9  5120.1  2405.2  5130.1 2406.43  5166.2 2412.05  5171.2 2412.24
  5180.2 2413.65  5190.2  2415.9  5230.3 2423.25  5247.8 2426.42  5250.3 2426.42
#Mann= 5 ,-1 , 0
  4799.3     .07       0  4910.9     .16       0  4987.8     .07       0
  4991.8     .16       0  5013.8     .07       0
Bank Sta=4987.8,4991.8
XS Rating Curve= 0 ,0
Exp/Cntr=0.3,0.1

Type RM Length L Ch R = 1 ,17627   ,499,499,499
BEGIN DESCRIPTION:
Bitter Creek Trib8T3 33.0
END DESCRIPTION:
XS GIS Cut Line= 3
      1434005.02      6820038.02      1434244.94      6820338.75
        1434205.        6820488.
#Sta/Elev= 30
  4615.3 2418.91  4618.5 2418.91  4622.5 2416.86  4628.9 2416.24  4651.3 2410.41
  4700.9 2404.03    4821 2397.68  4843.5 2392.82  4857.9 2391.78  4921.9 2388.85
    4986 2390.75  4992.4 2390.43  4996.3 2388.52  5002.2 2388.52  5007.6 2386.38
  5007.8 2385.88  5011.6 2386.38  5016.9 2388.85  5022.1 2388.27    5051 2396.63
    5057  2399.1  5062.1 2399.25  5071.7 2402.48    5082 2404.72    5097 2406.62
  5102.7 2409.86  5131.9 2419.34  5137.1 2419.79  5144.2 2422.76  5154.5 2424.84
#Mann= 3 ,-1 , 0
  4615.3     .07       0  5007.6     .07       0  5011.6     .07       0
Bank Sta=5007.6,5011.6
XS Rating Curve= 0 ,0
Exp/Cntr=0.3,0.1

Type RM Length L Ch R = 1 ,17128   ,473,473,473
BEGIN DESCRIPTION:
Bitter Creek Trib8T3 32.0
END DESCRIPTION:
XS GIS Cut Line= 3
      1433605.02      6820038.03      1433789.94      6820387.86
      1434005.02      6820588.02
#Sta/Elev= 30
  4604.3 2435.78  4626.9 2432.55  4634.4 2430.45  4656.5 2426.83  4672.1 2425.97
  4738.8 2418.18  4744.5 2416.81  4751.3 2413.71  4760.9 2411.69  4782.9 2409.43
  4804.9 2401.83  4832.5  2400.4  4870.9 2394.91  4914.9 2393.45    4921  2392.4
  4958.9 2390.25    4981 2387.76  4997.2  2384.6  5003.8  2385.4  5008.4 2383.36
  5008.7 2382.86  5012.9 2383.36  5032.1 2383.58  5053.1 2386.07  5109.8 2388.69
  5166.5 2397.16  5187.5 2401.92  5258.4 2425.96  5279.9 2429.49  5293.8 2430.09
#Mann= 3 ,-1 , 0
  4604.3     .07       0  5008.4     .07       0  5012.9     .07       0
Bank Sta=5008.4,5012.9
XS Rating Curve= 0 ,0
Exp/Cntr=0.3,0.1

Type RM Length L Ch R = 1 ,16655   ,493,493,493
BEGIN DESCRIPTION:
Bitter Creek Trib8T3 31.0
END DESCRIPTION:
XS GIS Cut Line= 3
      1433204.99        6820538.      1433374.44      6820567.45
      1433755.02      6820988.02
#Sta/Elev= 30
    4828 2418.52  4830.6 2418.52  4909.2 2397.44    4920 2392.13  4949.8 2382.67
  4961.7 2382.21  4969.5    2382  4980.3 2378.32  4988.1 2377.81  4988.4 2377.31
  4992.7 2377.81  5028.8 2381.09  5121.4 2381.67    5185 2383.82  5276.9 2390.58
  5347.9 2394.52  5390.4 2398.79  5425.6 2403.67  5439.8 2402.07  5446.5 2402.91
  5468.2 2402.09  5482.4 2402.81  5496.6 2406.33  5503.3 2410.98  5517.5 2414.75
  5539.1 2414.81  5545.9 2417.03  5553.3 2417.52  5560.1 2421.43  5567.2  2422.3
#Mann= 4 ,-1 , 0
    4828     .16       0  4961.7     .07       0  4988.1     .07       0
  4992.7     .07       0
Bank Sta=4988.1,4992.7
XS Rating Curve= 0 ,0
Exp/Cntr=0.3,0.1

Type RM Length L Ch R = 1 ,16162   ,473,473,473
BEGIN DESCRIPTION:
Bitter Creek Trib8T3 30.0
END DESCRIPTION:
XS GIS Cut Line= 3
      1433004.97      6820837.97       1433111.5      6820931.25
      1433404.97      6821237.97
#Sta/Elev= 30
  4858.4 2416.01  4861.8 2416.01  4865.6 2413.79  4879.8 2409.06  4900.7 2403.14
  4929.1 2397.05  4943.4 2392.03  4957.6 2385.74  4964.8 2379.83  4969.5 2371.02
  4969.9 2370.52  4974.2 2371.02  4976.9 2371.17  5014.3 2376.86  5078.1 2377.37
  5099.2 2379.46  5113.3 2379.34  5198.3 2383.59  5283.2 2389.28  5311.5 2395.36
  5339.8 2403.33  5346.7 2404.08  5353.9 2406.87  5360.9 2407.91  5382.2 2414.71
  5389.2 2415.85  5403.3 2421.61  5410.5 2423.18  5421.1 2427.05  5424.5 2427.05
#Mann= 4 ,-1 , 0
  4858.4     .16       0  4969.5     .07       0  4974.2     .16       0
  4976.9     .07       0
Bank Sta=4969.5,4974.2
XS Rating Curve= 0 ,0
Exp/Cntr=0.3,0.1

Type RM Length L Ch R = 1 ,15689   ,497,497,497
BEGIN DESCRIPTION:
Bitter Creek Trib8T3 29.0
END DESCRIPTION:
XS GIS Cut Line= 3
        1432605.        6821188.      1433004.94       6821367.8
      1433404.96      6821288.01
#Sta/Elev= 30
  4561.5 2414.22  4593.5  2402.9    4599 2402.46  4622.1 2394.88  4627.6 2394.96
  4668.4 2386.43    4726  2379.4    4772 2376.18  4795.2 2372.03  4812.9  2375.6
  4841.5 2375.67    4847 2373.87  4893.3 2374.19  4934.2 2370.83  4945.2 2368.03
  5002.6 2365.27  5017.5 2362.34  5017.9 2361.84  5022.5 2362.34  5025.1 2363.88
  5030.6 2363.31    5051 2372.11  5178.2  2383.7  5193.8 2389.52  5229.3 2393.64
  5234.6 2395.86  5280.3 2399.45  5331.4  2411.1  5367.2 2422.48  5407.9 2430.59
#Mann= 3 ,-1 , 0
  4561.5     .07       0  5017.5     .07       0  5022.5     .07       0
Bank Sta=5017.5,5022.5
XS Rating Curve= 0 ,0
Exp/Cntr=0.3,0.1

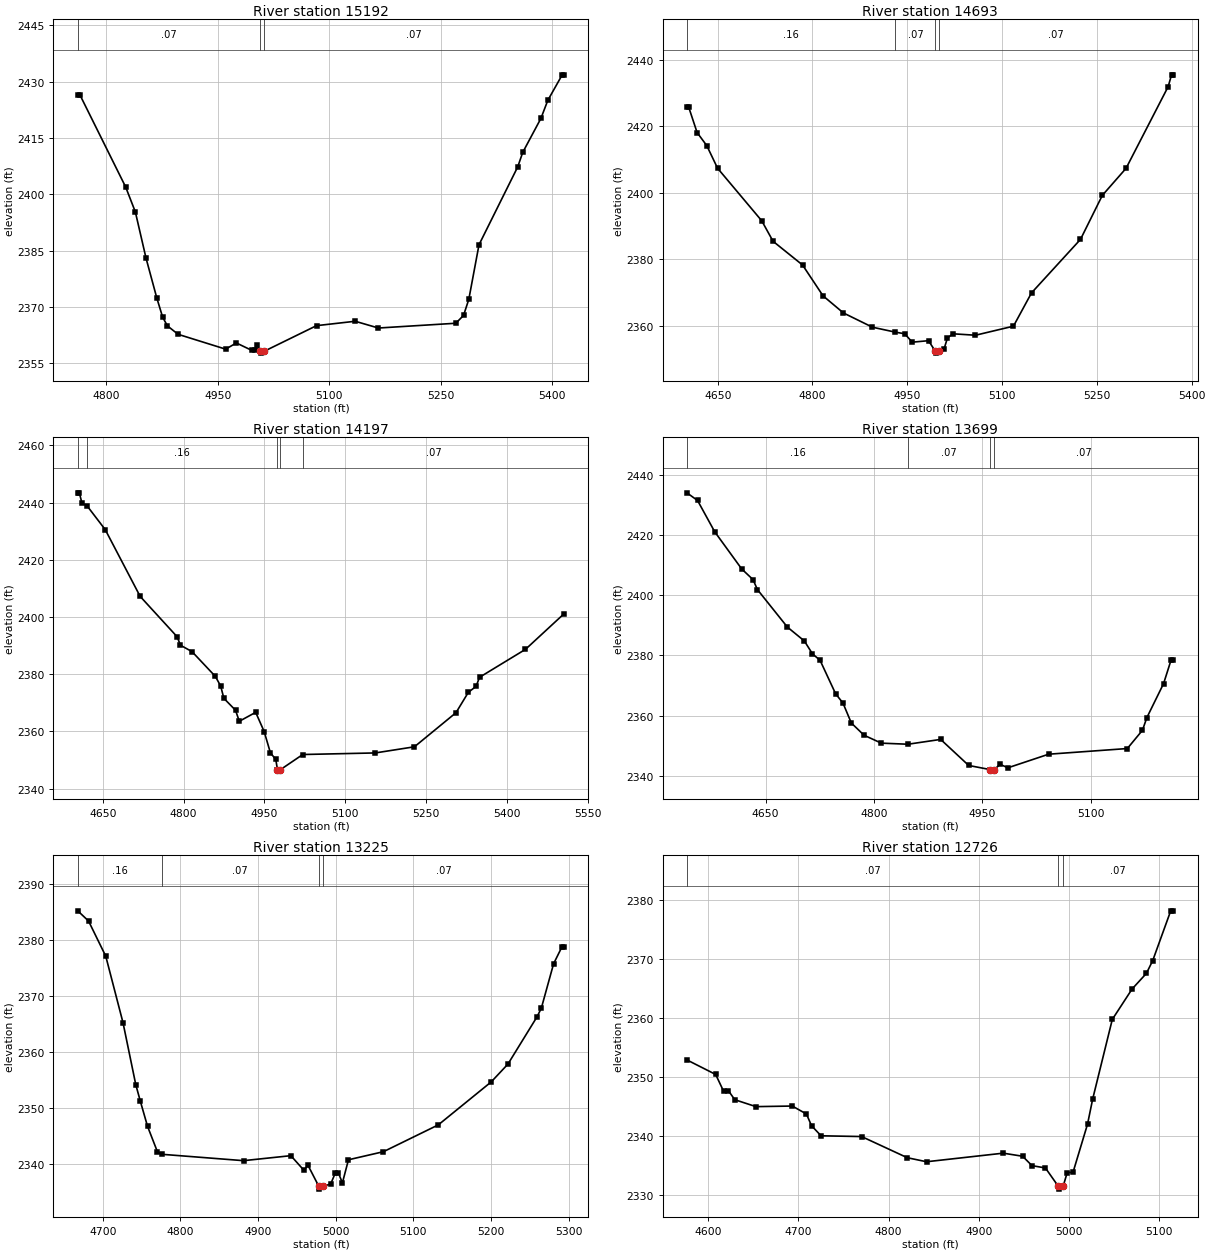
Type RM Length L Ch R = 1 ,15192   ,499,499,499
BEGIN DESCRIPTION:
Bitter Creek Trib8T3 28.0
END DESCRIPTION:
XS GIS Cut Line= 3
        1432505.        6821438.      1432689.72      6821588.39
        1432805.        6821988.
#Sta/Elev= 30
  4761.8 2426.39    4765 2426.39  4826.3 2401.93  4839.3 2395.29  4853.7 2382.95
  4868.1  2372.4    4876 2367.26  4882.4 2364.95  4896.8  2362.7  4960.7 2358.75
  4975.1  2360.4  4995.7 2358.44    5000 2358.44  5002.9 2359.87  5007.5 2358.19
  5007.9 2357.69  5012.6 2358.19  5082.9 2365.01  5134.9 2366.18  5166.1 2364.38
  5270.2 2365.65  5280.6 2367.73  5287.7 2372.03  5301.4 2386.56  5353.5 2407.33
  5360.2 2411.17  5384.7 2420.25  5393.9 2425.03  5413.3 2431.84  5415.9 2431.84
#Mann= 3 ,-1 , 0
  4761.8     .07       0  5007.5     .07       0  5012.6     .07       0
Bank Sta=5007.5,5012.6
XS Rating Curve= 0 ,0
Exp/Cntr=0.3,0.1

Type RM Length L Ch R = 1 ,14693   ,496,496,496
BEGIN DESCRIPTION:
Bitter Creek Trib8T3 27.0
END DESCRIPTION:
XS GIS Cut Line= 3
      1432255.01      6821538.04      1432375.09      6821918.23
      1432704.97      6822087.99
#Sta/Elev= 30
  4601.3 2425.91  4603.9 2425.91  4617.4 2418.15  4632.7 2414.22  4649.8 2407.42
  4719.7 2391.62  4737.6 2385.46  4784.3 2378.33  4816.7 2369.06    4849 2363.91
  4894.9 2359.63  4931.3 2358.14    4946 2357.66  4957.8 2355.13  4983.6 2355.58
  4994.6 2352.34    4995 2351.84  4999.9 2352.34    5008 2352.98  5013.6 2356.41
  5022.4 2357.65  5057.9 2357.22    5118 2359.94  5146.6 2369.95  5224.1 2386.04
  5258.6 2399.25  5296.2  2407.4  5362.8 2431.95  5368.2  2435.5    5371  2435.5
#Mann= 4 ,-1 , 0
  4601.3     .16       0  4931.3     .07       0  4994.6     .07       0
  4999.9     .07       0
Bank Sta=4994.6,4999.9
XS Rating Curve= 0 ,0
Exp/Cntr=0.3,0.1

Type RM Length L Ch R = 1 ,14197   ,498,498,498
BEGIN DESCRIPTION:
Bitter Creek Trib8T3 26.0
END DESCRIPTION:
XS GIS Cut Line= 3
      1431605.02      6821738.01      1431948.86      6821935.26
      1432255.01      6822338.01
#Sta/Elev= 30
  4603.6 2443.44  4606.5 2443.44  4611.5 2439.81    4621 2438.86  4654.6 2430.57
  4719.4 2407.22    4788  2393.1  4794.1 2390.16  4815.7 2387.89  4858.9 2379.24
  4868.7  2375.9  4874.7 2371.57  4896.3 2367.41  4903.3 2363.55  4933.7 2366.68
  4949.4 2359.97    4961 2352.53    4971 2350.19  4974.1 2346.62  4974.6 2346.12
  4979.5 2346.62    5021 2351.93  5155.5 2352.48  5228.2 2354.63  5305.3 2366.56
  5328.1 2373.65  5342.6 2375.79  5348.9 2378.93  5434.2 2388.71  5505.9 2401.19
#Mann= 5 ,-1 , 0
  4603.6     .07       0    4621     .16       0  4974.1     .07       0
  4979.5     .16       0    5021     .07       0
Bank Sta=4974.1,4979.5
XS Rating Curve= 0 ,0
Exp/Cntr=0.3,0.1

Type RM Length L Ch R = 1 ,13699   ,474,474,474
BEGIN DESCRIPTION:
Bitter Creek Trib8T3 25.0
END DESCRIPTION:
XS GIS Cut Line= 3
      1431504.99      6821887.97      1431681.73      6822311.36
      1431854.98      6822437.99
#Sta/Elev= 30
  4541.2 2433.96  4555.9 2431.42  4579.7 2421.02  4617.1 2408.67  4632.7 2405.15
  4638.8 2401.83  4680.3 2389.38  4703.8 2384.77    4715 2380.49  4725.5 2378.37
  4747.1 2367.22  4757.2 2364.18  4768.8 2357.54  4786.4 2353.48  4810.3 2350.85
  4847.2 2350.49  4892.5 2352.09  4931.3 2343.44  4961.2 2342.06  4961.6 2341.56
  4966.6 2342.06  4974.8 2343.83  4985.5 2342.66    5042 2347.18  5150.9 2349.06
  5171.8 2355.11    5178 2359.35  5201.1 2370.62  5211.5 2378.47  5214.6 2378.47
#Mann= 4 ,-1 , 0
  4541.2     .16       0  4847.2     .07       0  4961.2     .07       0
  4966.6     .07       0
Bank Sta=4961.2,4966.6
XS Rating Curve= 0 ,0
Exp/Cntr=0.3,0.1

Type RM Length L Ch R = 1 ,13225   ,499,499,499
BEGIN DESCRIPTION:
Bitter Creek Trib8T3 24.0
END DESCRIPTION:
XS GIS Cut Line= 3
      1431155.01      6822188.03       1431306.7       6822483.8
        1431455.        6822738.
#Sta/Elev= 30
  4667.6 2385.16  4681.5 2383.35  4703.7 2377.08  4725.9 2365.25  4742.4 2354.18
  4748.1 2351.32  4757.5 2346.78  4770.3 2342.22  4775.6 2341.79  4881.2 2340.65
  4942.2 2341.54  4958.8 2338.97  4964.4 2339.79  4978.2 2336.08  4978.7 2335.58
  4983.7 2336.08  4993.5 2336.49  4999.6 2338.51  5003.3 2338.51  5008.6 2336.69
  5016.4 2340.81  5061.5 2342.25  5132.2 2347.03  5200.4 2354.69  5221.9 2357.86
  5259.2 2366.24  5264.9 2367.81  5280.7 2375.73  5291.4 2378.72  5294.3 2378.72
#Mann= 4 ,-1 , 0
  4667.6     .16       0  4775.6     .07       0  4978.2     .07       0
  4983.7     .07       0
Bank Sta=4978.2,4983.7
XS Rating Curve= 0 ,0
Exp/Cntr=0.3,0.1

Type RM Length L Ch R = 1 ,12726   ,236,236,236
BEGIN DESCRIPTION:
Bitter Creek Trib8T3 23.0
END DESCRIPTION:
XS GIS Cut Line= 3
      1430955.02      6822388.04      1431099.17      6822786.47
      1431155.01      6822888.03
#Sta/Elev= 30
  4576.3 2352.92  4608.2 2350.46  4616.9 2347.65  4622.2 2347.74  4629.4 2346.19
  4652.9 2345.02  4693.2 2345.12  4708.9 2343.77  4714.5  2341.8  4725.1 2340.09
  4770.1 2339.96  4820.8 2336.38  4842.1  2335.7  4927.2 2337.15  4948.7 2336.63
  4959.1 2335.04    4974 2334.65  4988.2 2331.57  4988.6 2331.07  4993.7 2331.57
  4998.2 2333.88  5004.6  2333.9  5020.7 2342.05  5026.4 2346.29  5048.2 2359.77
  5070.2 2364.92    5086 2367.55    5093  2369.7    5113 2378.13  5115.9 2378.13
#Mann= 3 ,-1 , 0
  4576.3     .07       0  4988.2     .07       0  4993.7     .07       0
Bank Sta=4988.2,4993.7
XS Rating Curve= 0 ,0
Exp/Cntr=0.3,0.1

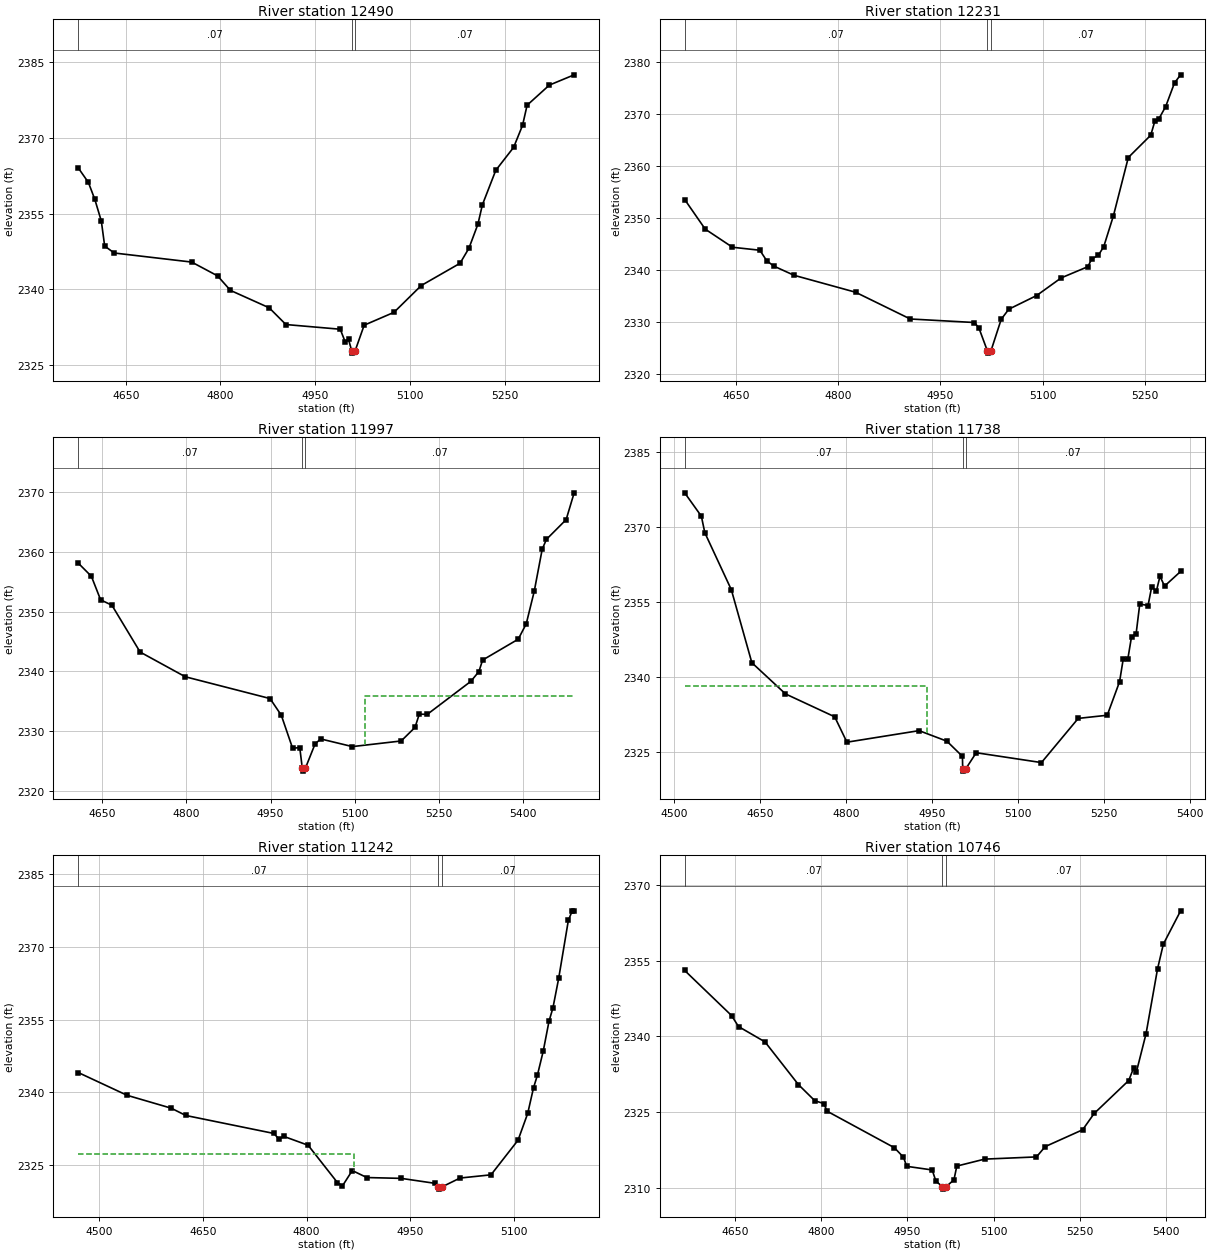
Type RM Length L Ch R = 1 ,12490   ,259,259,259
BEGIN DESCRIPTION:
Bitter Creek Trib8T3 4440
END DESCRIPTION:
XS GIS Cut Line= 4
      1430791.21      6822322.23      1430879.89      6822738.08
      1430933.36      6822878.92      1431079.83      6823028.64
#Sta/Elev= 30
  4574.8 2364.08  4590.9 2361.19  4601.1 2357.82  4611.4 2353.52  4616.7 2348.57
  4631.8 2347.19  4754.5 2345.39  4795.4 2342.66  4815.9 2339.77  4877.2 2336.32
  4903.7    2333  4989.7 2332.07  4997.4 2329.61  5002.8 2330.05  5007.8 2327.83
  5008.3 2327.33  5013.4 2327.83  5027.6 2332.87  5074.8 2335.42    5118 2340.74
  5179.4 2345.15  5193.5 2348.14  5207.7  2352.9  5214.8 2356.75    5236 2363.59
  5264.3 2368.15  5278.4 2372.52  5285.6  2376.5  5320.8 2380.49  5360.1 2382.53
#Mann= 3 ,-1 , 0
  4574.8     .07       0  5007.8     .07       0  5013.4     .07       0
Bank Sta=5007.8,5013.4
XS Rating Curve= 0 ,0
Exp/Cntr=0.3,0.1

Type RM Length L Ch R = 1 ,12231   ,234,234,234
BEGIN DESCRIPTION:
Bitter Creek Trib8T3 22.0
END DESCRIPTION:
XS GIS Cut Line= 3
        1430655.      6822388.01      1430681.82      6822811.96
      1430805.01      6823088.02
#Sta/Elev= 30
  4575.2 2353.61  4605.3 2347.91  4645.3 2344.42  4685.4 2343.85  4695.4 2341.85
  4705.5 2340.82  4735.5 2339.03  4825.7 2335.77  4905.9 2330.62    5000 2329.94
  5006.6 2328.88  5018.8 2324.55  5019.2 2324.05  5024.4 2324.55  5039.3 2330.57
  5050.4  2332.5  5091.2 2335.13  5127.1 2338.52  5166.4 2340.69  5171.8 2342.14
  5181.8 2342.89  5189.6 2344.55  5203.7 2350.44  5225.6 2361.69  5258.5 2365.98
  5264.7 2368.77  5270.2 2369.08  5280.4  2371.5  5293.4 2376.07  5302.3  2377.6
#Mann= 3 ,-1 , 0
  4575.2     .07       0  5018.8     .07       0  5024.4     .07       0
Bank Sta=5018.8,5024.4
XS Rating Curve= 0 ,0
Exp/Cntr=0.3,0.1

Type RM Length L Ch R = 1 ,11997   ,259,259,259
BEGIN DESCRIPTION:
Bitter Creek Trib8T3 4441
END DESCRIPTION:
XS GIS Cut Line= 4
      1430542.73      6822348.34      1430494.36      6822738.56
      1430504.76      6822917.98      1430740.56      6823122.56
#Sta/Elev= 30
  4606.8 2358.12  4630.3 2355.91  4646.8 2351.97  4666.9 2351.08  4717.3 2343.25
  4797.9 2339.12  4949.1 2335.48  4969.2  2332.7  4989.4 2327.18  5002.2 2327.28
  5006.7 2323.85  5007.1 2323.35  5012.3 2323.85  5029.5 2327.89  5039.5 2328.73
  5096.1 2327.45  5183.2 2328.39  5207.9 2330.66  5215.5 2332.87  5229.8 2332.84
  5307.6 2338.36  5321.9 2339.99  5328.5 2341.91  5392.1  2345.4  5406.4 2347.97
  5420.6 2353.38  5434.9 2360.44  5442.5 2362.09  5477.6 2365.38  5491.9 2369.86
#Mann= 3 ,-1 , 0
  4606.8     .07       0  5006.7     .07       0  5012.3     .07       0
#XS Ineff= 2 , 0
                         5117.77         2335.84
Permanent Ineff=
       F       F
Bank Sta=5006.7,5012.3
XS Rating Curve= 0 ,0
Exp/Cntr=0.3,0.1

Type RM Length L Ch R = 1 ,11738   ,496,496,496
BEGIN DESCRIPTION:
Bitter Creek Trib8T3 21.0
END DESCRIPTION:
XS GIS Cut Line= 3
      1430054.99      6822487.99       1430305.4      6822899.02
      1430604.97      6823137.98
#Sta/Elev= 30
  4518.7 2376.83  4547.8 2372.15  4553.8 2368.85    4600 2357.45  4635.8 2342.84
  4694.4  2336.6  4780.2 2332.02  4801.5 2326.94  4927.3 2329.25  4975.8 2327.14
  5002.9  2324.1  5003.3 2321.65  5003.8 2321.15  5008.9 2321.65  5026.9 2324.83
  5140.6 2322.86  5204.7  2331.7  5255.3 2332.33  5276.8 2339.05  5283.2 2343.61
  5291.2 2343.61  5297.6 2348.02  5305.6 2348.62    5312  2354.6  5326.4 2354.27
  5332.8 2358.05  5340.8 2357.09  5347.2 2360.14  5355.2 2358.17  5383.2  2361.1
#Mann= 3 ,-1 , 0
  4518.7     .07       0  5003.3     .07       0  5008.9     .07       0
#XS Ineff= 2 , 0
         4941.12 2338.27
Permanent Ineff=
       F       F
Bank Sta=5003.3,5008.9
XS Rating Curve= 0 ,0
Exp/Cntr=0.3,0.1

Type RM Length L Ch R = 1 ,11242   ,496,496,496
BEGIN DESCRIPTION:
Bitter Creek Trib8T3 20.0
END DESCRIPTION:
XS GIS Cut Line= 3
      1429755.01      6822788.01      1430121.57      6823171.09
        1430205.        6823338.
#Sta/Elev= 30
  4469.8  2344.1  4540.4 2339.42  4604.2 2336.77  4625.3 2335.27  4752.7 2331.57
  4759.9  2330.4  4766.8 2330.98  4802.1 2329.15  4844.5 2321.47  4851.7 2320.79
  4865.9 2323.95    4887 2322.51  4936.7 2322.34    4986 2321.31  4990.5 2320.63
  4990.9 2320.13  4996.1 2320.63  5021.7 2322.41  5066.4 2323.07  5105.5 2330.19
  5119.5 2335.71  5127.9 2340.98  5133.5 2343.56  5141.9 2348.49  5150.3 2354.67
  5155.9 2357.37  5164.2 2363.43  5178.2 2375.36  5183.8 2377.34  5186.6 2377.34
#Mann= 3 ,-1 , 0
  4469.8     .07       0  4990.5     .07       0  4996.1     .07       0
#XS Ineff= 2 , 0
         4867.82 2327.28
Permanent Ineff=
       F       F
Bank Sta=4990.5,4996.1
XS Rating Curve= 0 ,0
Exp/Cntr=0.3,0.1

Type RM Length L Ch R = 1 ,10746   ,498,498,498
BEGIN DESCRIPTION:
Bitter Creek Trib8T3 19.0
END DESCRIPTION:
XS GIS Cut Line= 3
      1429354.96      6823187.97      1429731.04      6823410.92
      1430154.98        6823438.
#Sta/Elev= 30
  4562.8 2353.05  4644.2 2344.12  4656.4 2341.93  4702.4 2338.89  4760.5 2330.42
    4789 2327.22  4804.6 2326.66  4810.4 2325.14  4927.3  2317.9    4943 2316.03
  4948.8 2314.21    4993 2313.49  4999.4 2311.28  5010.7 2310.19  5011.2 2309.69
  5017.2 2310.19  5030.8 2311.52  5035.8 2314.26  5084.1 2315.64  5174.3 2316.08
  5189.4 2318.12  5254.5 2321.46  5274.5 2324.69  5334.6 2331.23    5343 2333.68
    5348 2332.96  5364.7  2340.5  5384.7 2353.38  5394.8 2358.28  5424.8 2364.88
#Mann= 3 ,-1 , 0
  4562.8     .07       0  5010.7     .07       0  5017.2     .07       0
Bank Sta=5010.7,5017.2
XS Rating Curve= 0 ,0
Exp/Cntr=0.3,0.1

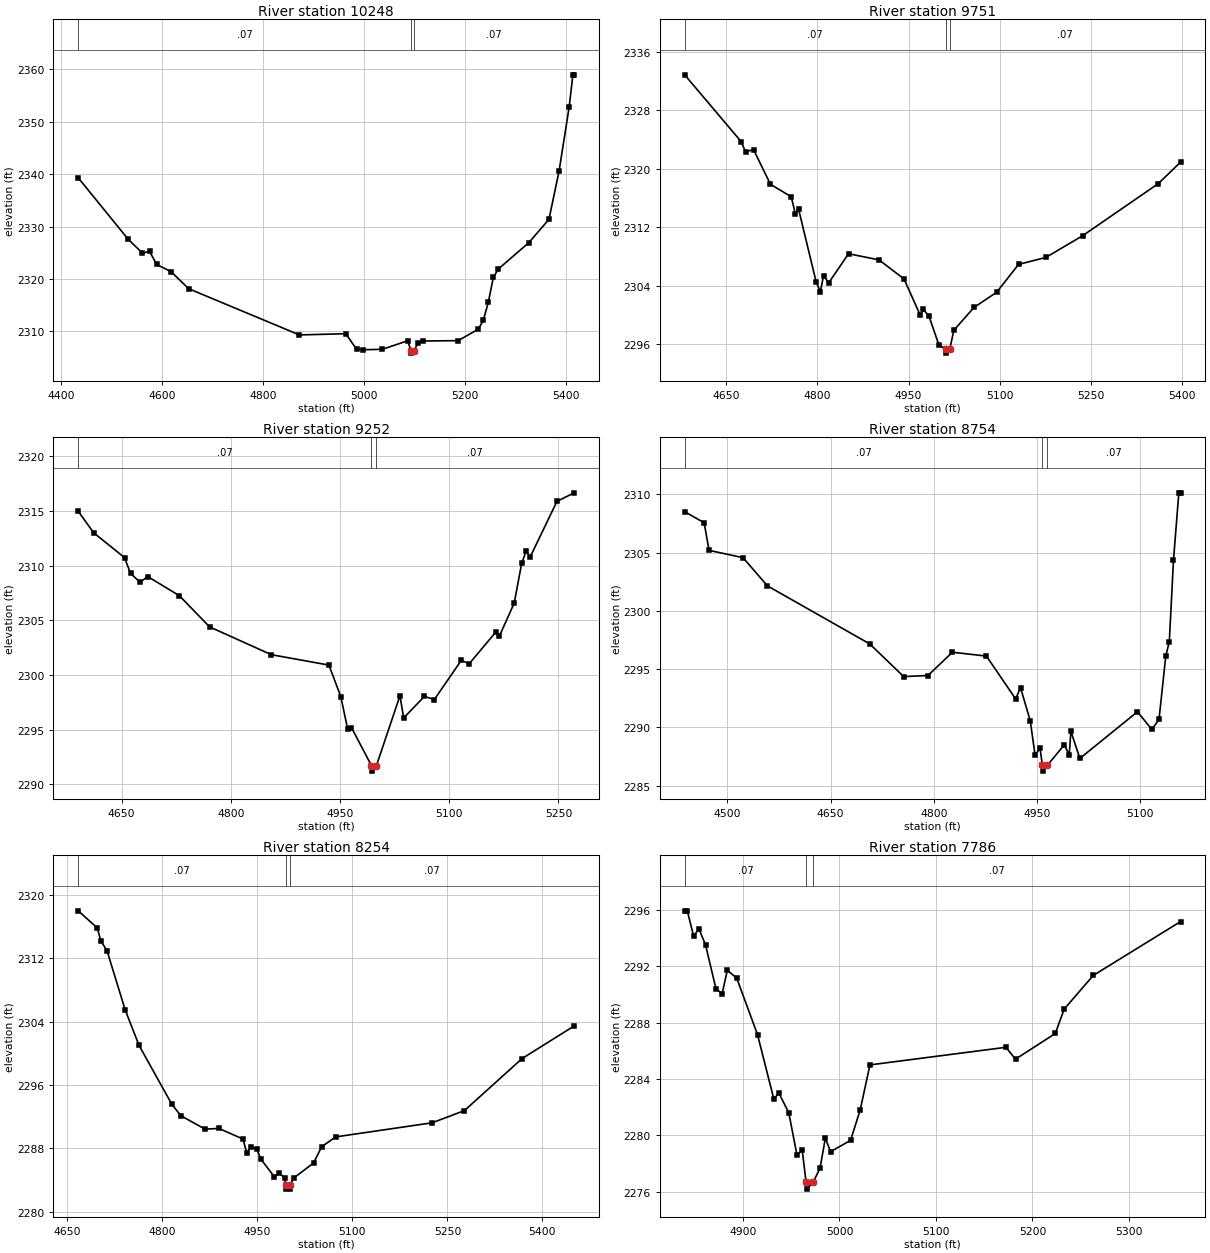
Type RM Length L Ch R = 1 ,10248   ,497,497,497
BEGIN DESCRIPTION:
Bitter Creek Trib8T3 18.0
END DESCRIPTION:
XS GIS Cut Line= 3
      1429355.03      6823388.03      1429738.53      6823805.12
      1430154.98        6823788.
#Sta/Elev= 30
  4433.4  2339.3  4532.3  2327.6  4560.7 2324.94  4574.9 2325.26    4589 2322.77
  4617.4 2321.41  4652.5 2318.15    4872 2309.34  4963.9 2309.57  4985.5  2306.6
  4998.6 2306.51  5036.5  2306.6  5086.5 2308.22  5093.3 2306.37  5093.8 2305.87
  5099.9 2306.37  5106.6 2307.74  5116.6 2308.18  5186.6 2308.25  5226.7 2310.42
  5236.7 2312.15  5246.7 2315.61  5256.7 2320.37  5266.7 2321.93  5326.7 2326.91
  5366.8 2331.37  5386.8 2340.53  5406.8 2352.73  5414.3 2358.93  5416.8 2358.93
#Mann= 3 ,-1 , 0
  4433.4     .07       0  5093.3     .07       0  5099.9     .07       0
Bank Sta=5093.3,5099.9
XS Rating Curve= 0 ,0
Exp/Cntr=0.3,0.1

Type RM Length L Ch R = 1 ,9751    ,499,499,499
BEGIN DESCRIPTION:
Bitter Creek Trib8T3 17.0
END DESCRIPTION:
XS GIS Cut Line= 3
      1429255.04      6824038.01      1429660.85      6824140.29
      1430054.99        6824088.
#Sta/Elev= 30
  4581.5 2332.83  4674.3 2323.72  4681.6 2322.33  4694.9  2322.6  4722.7 2317.87
  4756.8 2316.18  4763.8 2313.77  4768.9 2314.49    4798 2304.48  4804.8 2303.22
    4810 2305.36  4818.7 2304.43  4851.1 2308.39  4901.2 2307.55  4942.4 2304.95
  4969.2 2299.98  4974.3 2300.78  4983.7 2299.82  4999.6 2295.98  5010.9 2295.31
  5011.4 2294.81  5017.6 2295.31  5024.4 2297.93  5057.6 2301.05    5095 2303.13
  5130.9 2306.93  5175.7 2307.88  5236.2 2310.84  5360.9 2317.97  5397.6 2320.91
#Mann= 3 ,-1 , 0
  4581.5     .07       0  5010.9     .07       0  5017.6     .07       0
Bank Sta=5010.9,5017.6
XS Rating Curve= 0 ,0
Exp/Cntr=0.3,0.1

Type RM Length L Ch R = 1 ,9252    ,498,498,498
BEGIN DESCRIPTION:
Bitter Creek Trib8T3 16.0
END DESCRIPTION:
XS GIS Cut Line= 3
      1429355.03      6824438.01      1429740.95      6824574.96
      1430005.03      6824638.01
#Sta/Elev= 30
  4590.5 2314.97  4611.7    2313  4654.1 2310.73  4662.3 2309.29  4675.4 2308.48
    4686    2309  4729.4 2307.25  4770.9  2304.4  4855.7 2301.86  4934.8 2300.91
  4951.2    2298  4960.4 2295.08  4965.7  2295.2  4993.2 2291.72  4993.7 2291.22
    5000 2291.72  5032.3 2298.11  5037.4 2296.08  5065.9 2298.05  5079.5 2297.76
  5116.4 2301.33  5127.5 2301.04  5163.7 2303.91  5168.8 2303.55  5189.2 2306.58
  5199.5 2310.23  5205.8 2311.37  5210.9 2310.76  5247.9 2315.87  5271.5 2316.65
#Mann= 3 ,-1 , 0
  4590.5     .07       0  4993.2     .07       0    5000     .07       0
Bank Sta=4993.2,5000
XS Rating Curve= 0 ,0
Exp/Cntr=0.3,0.1

Type RM Length L Ch R = 1 ,8754    ,500,500,500
BEGIN DESCRIPTION:
Bitter Creek Trib8T3 15.0
END DESCRIPTION:
XS GIS Cut Line= 3
      1429404.99      6824587.99      1429803.53      6824984.39
      1429954.98        6824938.
#Sta/Elev= 30
  4437.9 2308.52  4466.2 2307.57  4473.3  2305.2  4522.7 2304.57  4558.1 2302.15
  4706.6 2297.17  4756.1 2294.36  4791.4 2294.45  4826.8 2296.45  4876.3 2296.12
  4918.7 2292.44  4925.8 2293.41    4940 2290.55    4947 2287.59  4954.1 2288.22
  4957.6 2286.74  4958.1 2286.24  4964.8 2286.74  4989.4  2288.5  4996.5 2287.64
    4999 2289.66    5012 2287.33  5095.7 2291.34  5116.6 2289.82    5127 2290.68
  5136.8 2296.11    5142 2297.37    5148 2304.33  5155.8 2310.14  5158.4 2310.14
#Mann= 3 ,-1 , 0
  4437.9     .07       0  4957.6     .07       0  4964.8     .07       0
Bank Sta=4957.6,4964.8
XS Rating Curve= 0 ,0
Exp/Cntr=0.3,0.1

Type RM Length L Ch R = 1 ,8254    ,468,468,468
BEGIN DESCRIPTION:
Bitter Creek Trib8T3 14.0
END DESCRIPTION:
XS GIS Cut Line= 3
      1429154.96      6825087.98      1429448.51      6825244.77
      1429855.02      6825438.01
#Sta/Elev= 30
  4667.2 2317.98  4697.3 2315.82    4703 2314.16  4712.6 2312.97  4741.2 2305.51
  4763.2    2301  4814.6 2293.62    4829 2292.14  4867.3 2290.43  4889.2 2290.52
  4927.4 2289.18  4933.1 2287.44  4939.3 2288.14  4949.4  2287.9  4955.1 2286.69
    4977  2284.4  4984.7 2284.84  4993.3 2284.29  4994.5 2283.36    4995 2282.86
  5001.3 2282.86  5001.8 2283.36  5007.2 2284.25  5038.7 2286.15  5051.5 2288.21
  5073.6 2289.45  5225.9 2291.23  5276.9 2292.77  5367.8 2299.33  5450.1 2303.45
#Mann= 3 ,-1 , 0
  4667.2     .07       0  4994.5     .07       0  5001.8     .07       0
Bank Sta=4994.5,5001.8
XS Rating Curve= 0 ,0
Exp/Cntr=0.3,0.1

Type RM Length L Ch R = 1 ,7786    ,500,500,500
BEGIN DESCRIPTION:
Bitter Creek Trib8T3 13.0
END DESCRIPTION:
XS GIS Cut Line= 3
      1429055.03      6825438.01      1429203.61      6825498.43
      1429554.99        6825538.
#Sta/Elev= 30
  4839.6 2295.93  4842.3 2295.93  4848.9 2294.12  4854.3 2294.66  4861.2 2293.52
    4872  2290.4  4878.4 2290.04  4883.8 2291.71  4893.5 2291.16  4915.1 2287.14
  4931.9 2282.59  4937.3 2282.98  4947.5 2281.59    4956 2278.58  4961.4 2278.95
  4965.4 2276.67  4965.9 2276.17  4972.8 2276.67  4979.9 2277.66  4985.4 2279.79
  4990.8 2278.83  5011.5 2279.63  5021.5 2281.79  5031.6 2284.99  5172.5 2286.24
  5182.5  2285.4  5223.7 2287.22  5232.9 2288.95    5263 2291.34  5353.6 2295.17
#Mann= 3 ,-1 , 0
  4839.6     .07       0  4965.4     .07       0  4972.8     .07       0
Bank Sta=4965.4,4972.8
XS Rating Curve= 0 ,0
Exp/Cntr=0.3,0.1

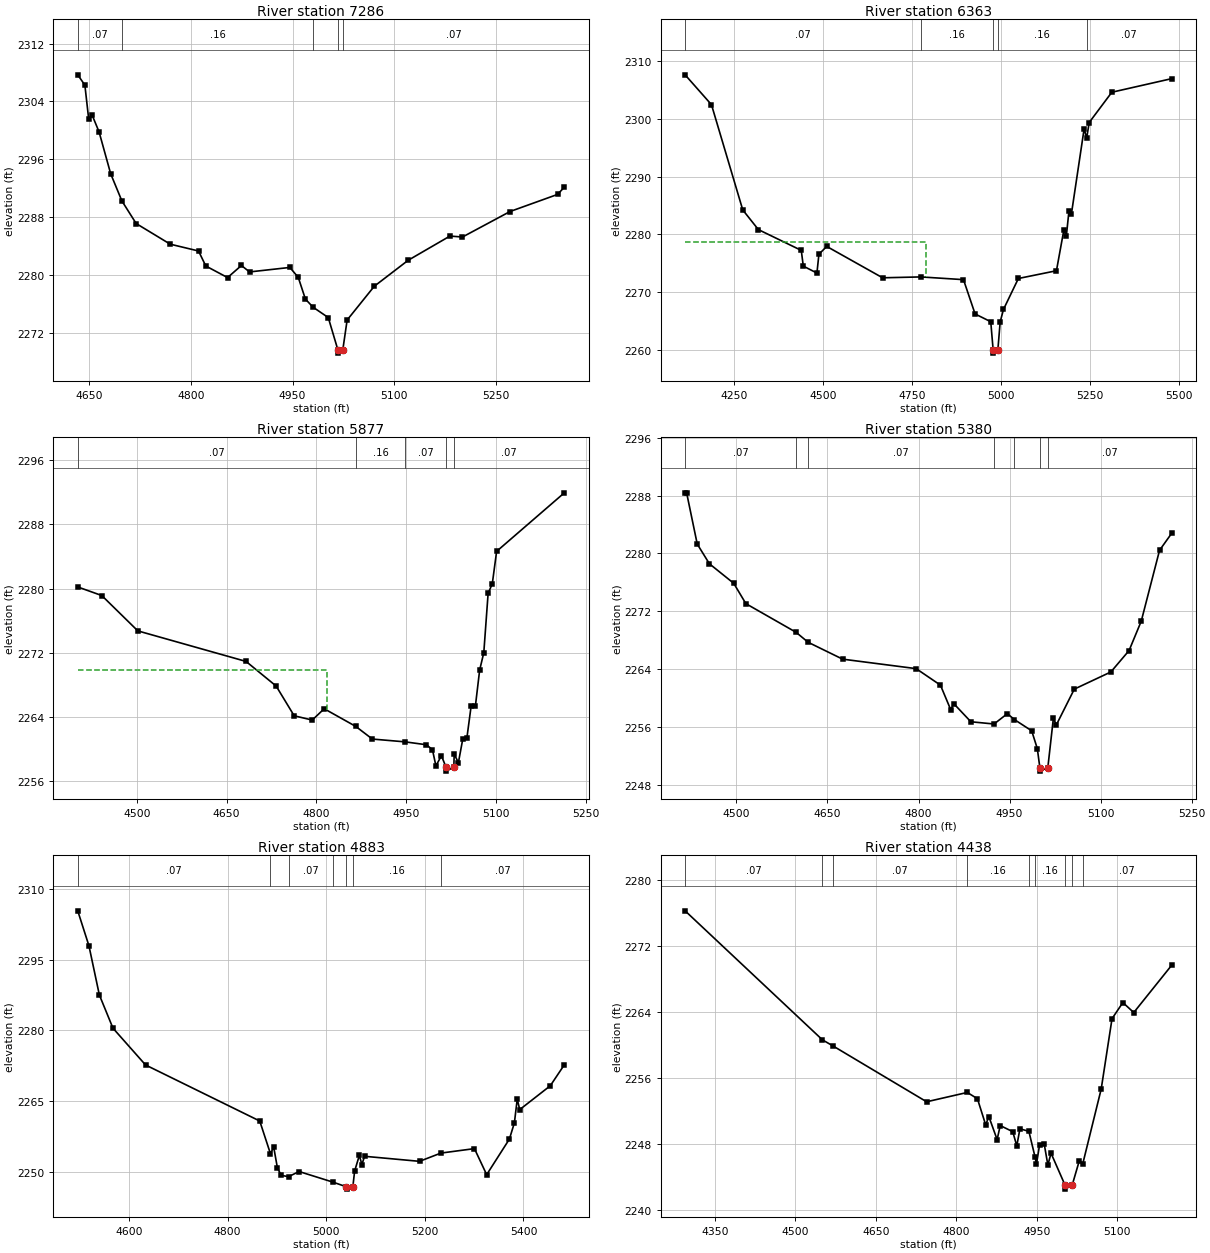
Type RM Length L Ch R = 1 ,7286    ,923,923,923
BEGIN DESCRIPTION:
Bitter Creek Trib8T3 12.0
END DESCRIPTION:
XS GIS Cut Line= 3
        1428855.        6825888.      1429204.54      6825998.19
        1429555.        6825988.
#Sta/Elev= 30
  4633.5 2307.68    4644 2306.26  4649.7 2301.52  4654.9 2302.08    4665 2299.78
    4682 2294.03  4698.5 2290.28  4719.6 2287.15  4769.8  2284.3  4811.5 2283.36
  4822.2 2281.29  4854.3 2279.69  4874.7 2281.36  4886.7 2280.47  4946.1 2281.09
  4958.5 2279.71    4969 2276.72  4980.3  2275.6  5002.7 2274.17  5016.7 2269.76
  5017.2 2269.26  5024.2 2269.76  5030.5 2273.83  5070.5 2278.49  5120.5 2282.08
    5182 2285.42  5200.5 2285.29  5270.6 2288.81  5340.6 2291.17  5350.6 2292.17
#Mann= 5 ,-1 , 0
  4633.5     .07       0  4698.5     .16       0  4980.3     .07       0
  5016.7     .07       0  5024.2     .07       0
Bank Sta=5016.7,5024.2
XS Rating Curve= 0 ,0
Exp/Cntr=0.3,0.1

Type RM Length L Ch R = 1 ,6363    ,486,486,486
BEGIN DESCRIPTION:
Bitter Creek Trib8T3 11.0
END DESCRIPTION:
XS GIS Cut Line= 3
        1428805.        6825938.      1429221.57      6826721.09
      1429540.67      6827079.93
#Sta/Elev= 30
    4113 2307.58  4187.1 2302.42    4275 2284.23  4318.9 2280.83  4439.4 2277.24
  4445.1 2274.52  4483.4 2273.32    4489 2276.58    4511 2277.92    4668  2272.5
  4775.2 2272.65  4895.2 2272.18  4927.8 2266.25  4971.8 2264.91  4978.6 2259.98
  4979.1 2259.48  4991.7 2259.98  4998.3 2264.88  5007.6 2267.04  5049.4 2272.38
  5156.4 2273.72  5177.4 2280.83  5184.1 2279.67  5191.6 2284.07  5198.3 2283.48
  5234.2 2298.26  5241.3 2296.64  5248.4 2299.34    5312 2304.57  5480.2 2306.92
#Mann= 5 ,-1 , 0
    4113     .07       0  4775.2     .16       0  4978.6     .07       0
  4991.7     .16       0  5241.3     .07       0
#XS Ineff= 2 , 0
         4789.44 2278.64
Permanent Ineff=
       F       F
Bank Sta=4978.6,4991.7
XS Rating Curve= 0 ,0
Exp/Cntr=0.3,0.1

Type RM Length L Ch R = 1 ,5877    ,497,497,497
BEGIN DESCRIPTION:
Bitter Creek Trib8T3 10.0
END DESCRIPTION:
XS GIS Cut Line= 3
        1428805.      6826188.04      1428756.46      6826784.46
      1428904.98      6826937.98
#Sta/Elev= 30
  4401.6  2280.2  4441.7 2279.13  4501.9 2274.72  4682.5 2270.91  4732.7 2267.84
  4762.8 2264.13  4792.9  2263.6  4812.9 2265.01  4865.5 2262.81  4893.2 2261.23
  4947.9 2260.88  4983.5 2260.52  4993.5  2259.9  4999.3 2257.89  5008.5 2259.15
  5016.1 2257.73  5016.6 2257.23  5029.2 2257.73  5029.8 2259.37  5036.8 2258.28
    5044 2261.19  5050.9 2261.32  5058.1 2265.36  5065.1  2265.3  5072.3 2269.84
  5079.2    2272  5086.4 2279.39  5093.4 2280.61  5100.6 2284.64  5213.6 2291.94
#Mann= 5 ,-1 , 0
  4401.6     .07       0  4865.5     .16       0  4947.9     .07       0
  5016.1     .07       0  5029.2     .07       0
#XS Ineff= 2 , 0
         4817.26  2269.9
Permanent Ineff=
       F       F
Bank Sta=5016.1,5029.2
XS Rating Curve= 0 ,0
Exp/Cntr=0.3,0.1

Type RM Length L Ch R = 1 ,5380    ,497,497,497
BEGIN DESCRIPTION:
Bitter Creek Trib8T3 9.0
END DESCRIPTION:
XS GIS Cut Line= 3
        1428305.      6826088.04      1428338.25       6826671.6
        1428355.      6826887.95
#Sta/Elev= 30
  4415.5 2288.38    4418 2288.38  4435.5  2281.3  4455.5 2278.58  4495.6 2275.88
  4515.6 2273.07  4598.3 2269.11  4618.2 2267.73    4675  2265.4  4796.1 2264.09
  4836.1 2261.81  4853.1  2258.4  4858.1 2259.25  4886.2 2256.75  4924.4 2256.44
  4946.3 2257.87    4958 2257.05  4986.4  2255.5  4995.7 2253.03  4999.8 2250.43
  5000.3 2249.93    5013 2250.43  5022.1 2257.22  5027.1 2256.33  5056.6 2261.26
  5116.8 2263.63  5146.8 2266.59  5166.9 2270.66    5197 2280.44    5217 2282.79
#Mann= 7 ,-1 , 0
  4415.5     .07       0  4598.3     .16       0  4618.2     .07       0
  4924.4     .16       0    4958     .07       0  4999.8     .07       0
    5013     .07       0
Bank Sta=4999.8,5013
XS Rating Curve= 0 ,0
Exp/Cntr=0.3,0.1

Type RM Length L Ch R = 1 ,4883    ,445,445,445
BEGIN DESCRIPTION:
Bitter Creek Trib8T3 8.0
END DESCRIPTION:
XS GIS Cut Line= 3
      1428254.98      6826038.03      1427981.34      6826461.16
        1427905.      6826937.99
#Sta/Elev= 30
  4496.1 2305.39  4518.8 2297.97  4539.9 2287.54  4567.5 2280.48  4633.6 2272.67
  4865.2 2260.77  4886.9 2253.83  4893.5 2255.23    4901 2250.83  4908.7 2249.23
  4923.7 2248.96  4944.9 2250.05  5014.4 2247.77  5040.8 2246.81  5041.3 2246.31
    5054 2246.81  5057.6 2250.13  5067.2 2253.49  5072.3 2251.53  5077.8 2253.28
  5189.2 2252.21  5232.5 2253.96  5300.6 2254.91  5325.4 2249.38  5371.5 2256.94
  5381.6 2260.38  5387.4 2265.42  5392.4 2263.19  5454.4 2268.25  5482.9 2272.71
#Mann= 7 ,-1 , 0
  4496.1     .07       0  4886.9     .16       0  4923.7     .07       0
  5014.4     .16       0  5040.8     .07       0    5054     .16       0
  5232.5     .07       0
Bank Sta=5040.8,5054
XS Rating Curve= 0 ,0
Exp/Cntr=0.3,0.1

Type RM Length L Ch R = 1 ,4438    ,499,499,499
BEGIN DESCRIPTION:
Bitter Creek Trib8T3 7.0
END DESCRIPTION:
XS GIS Cut Line= 3
      1428055.02      6826087.96       1427685.1      6826688.82
      1427655.01      6826887.95
#Sta/Elev= 30
  4294.4 2276.23  4550.4  2260.6  4570.7 2259.84  4744.6  2253.1  4820.4 2254.23
  4839.3 2253.47  4854.7  2250.3  4860.6 2251.31    4876 2248.52  4881.8 2250.22
  4905.1 2249.48  4912.7 2247.76  4918.5 2249.83  4935.2 2249.52  4946.8 2246.39
  4949.3 2245.53  4955.2 2247.91  4963.8 2247.98  4970.6 2245.44  4976.5 2246.87
  5002.5 2243.02    5003 2242.52    5016 2243.02  5029.3 2245.98  5035.5 2245.55
    5070 2254.64  5090.2 2263.17  5110.4 2265.12  5130.7 2263.91  5201.4 2269.64
#Mann= 9 ,-1 , 0
  4294.4     .07       0  4550.4     .16       0  4570.7     .07       0
  4820.4     .16       0  4935.2     .07       0  4946.8     .16       0
  5002.5     .07       0    5016     .16       0  5035.5     .07       0
Bank Sta=5002.5,5016
XS Rating Curve= 0 ,0
Exp/Cntr=0.3,0.1