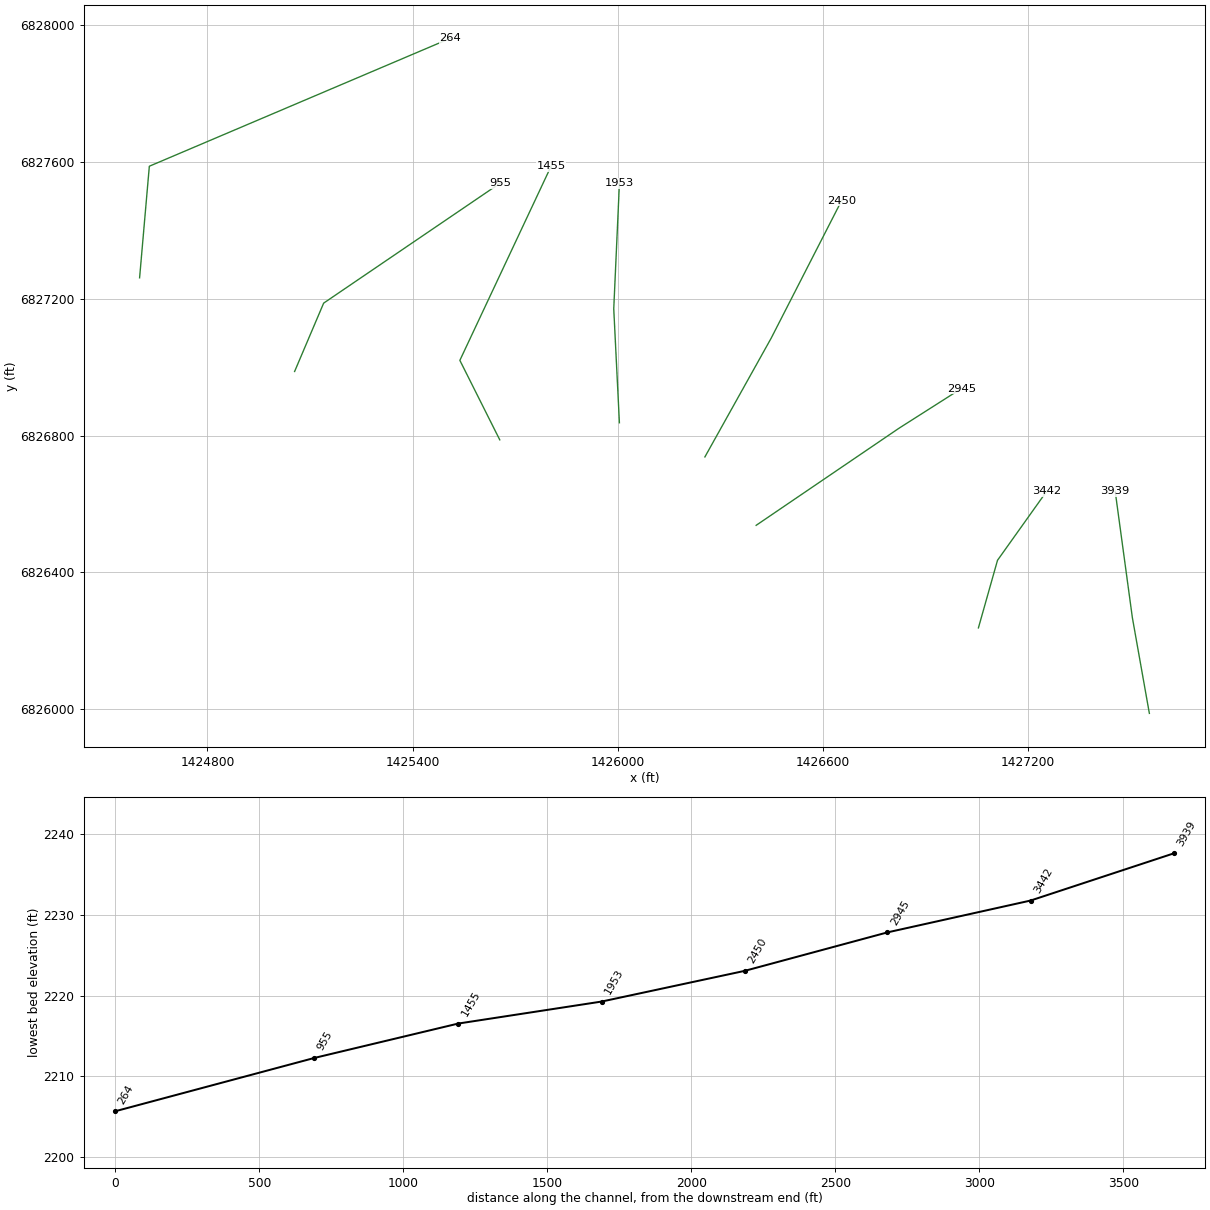
HEC-RAS study Bitter Creek Trib8T3.prj: Bitter Creek Trib8T3 Base Level Engineering

--- Bitter Creek Trib8T3.g01 (geometry) --- (continued)

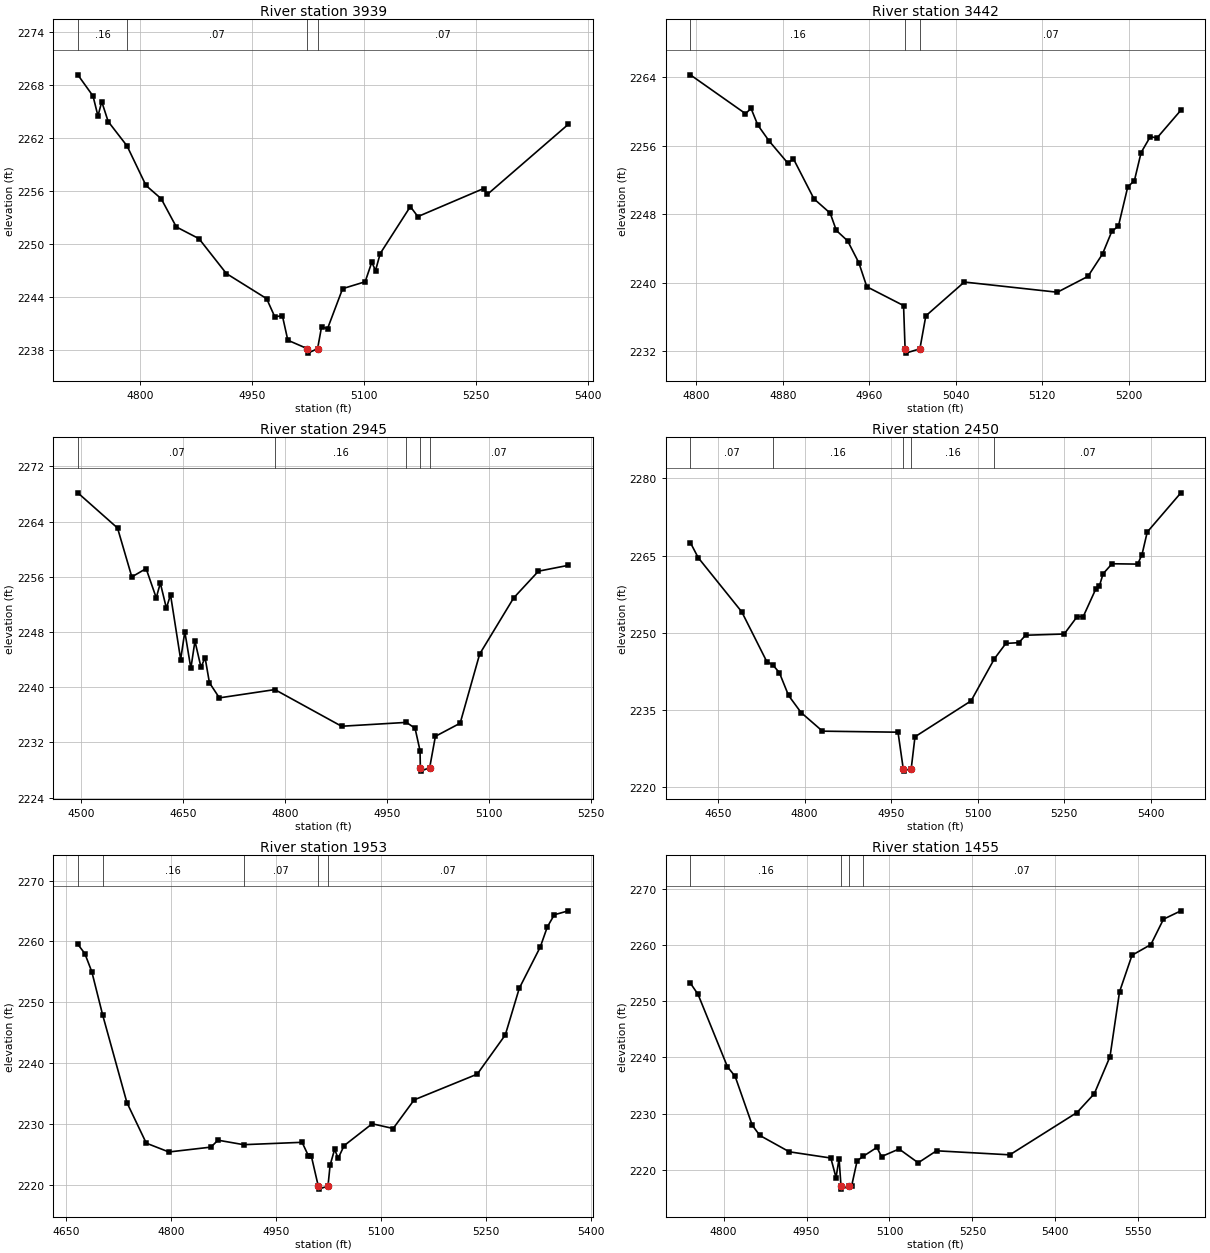
Type RM Length L Ch R = 1 ,3939    ,497,497,497
BEGIN DESCRIPTION:
Bitter Creek Trib8T3 6.0
END DESCRIPTION:
XS GIS Cut Line= 3
      1427555.01      6825987.96      1427505.37      6826267.49
        1427455.      6826637.98
#Sta/Elev= 30
  4716.1 2269.12  4736.5 2266.72  4743.1 2264.47  4748.2 2266.08  4756.8 2263.84
  4782.1 2261.08  4807.5 2256.61  4827.9 2255.11  4848.2 2251.92  4878.6 2250.59
  4915.3 2246.65  4969.3 2243.81  4980.2 2241.76  4990.4 2241.88  4997.7 2239.11
    5024 2238.15  5024.5 2237.65  5037.6 2238.15  5042.9  2240.6    5051 2240.43
  5071.2 2244.94  5101.4 2245.72  5110.3 2247.93  5115.3 2246.99  5121.6 2248.91
    5162 2254.22  5172.1 2253.09  5260.2 2256.26  5265.3  2255.6  5373.9 2263.53
#Mann= 4 ,-1 , 0
  4716.1     .16       0  4782.1     .07       0    5024     .07       0
  5037.6     .07       0
Bank Sta=5024,5037.6
XS Rating Curve= 0 ,0
Exp/Cntr=0.3,0.1

Type RM Length L Ch R = 1 ,3442    ,497,497,497
BEGIN DESCRIPTION:
Bitter Creek Trib8T3 5.0
END DESCRIPTION:
XS GIS Cut Line= 3
      1427054.99      6826237.95      1427110.86      6826435.71
      1427255.01      6826638.01
#Sta/Elev= 30
  4794.5 2264.29  4845.5 2259.76  4850.7 2260.36  4856.9 2258.43  4867.3 2256.58
  4884.7 2253.98  4889.9 2254.48  4908.9 2249.81  4923.9 2248.14  4929.6 2246.12
    4940 2244.91  4950.4 2242.35  4957.8 2239.55  4991.8 2237.35  4993.2  2232.3
  4993.7  2231.8  5006.9  2232.3  5012.4 2236.15    5048  2240.1  5134.1 2238.91
  5162.4 2240.76  5175.9 2243.38  5184.5 2246.02  5190.6 2246.63  5199.2 2251.19
  5205.4 2251.95  5211.6 2255.22  5220.1 2257.07  5226.3 2256.92  5248.4 2260.16
#Mann= 3 ,-1 , 0
  4794.5     .16       0  4993.2     .07       0  5006.9     .07       0
Bank Sta=4993.2,5006.9
XS Rating Curve= 0 ,0
Exp/Cntr=0.3,0.1

Type RM Length L Ch R = 1 ,2945    ,495,495,495
BEGIN DESCRIPTION:
Bitter Creek Trib8T3 4.0
END DESCRIPTION:
XS GIS Cut Line= 3
      1426404.96      6826537.97      1426822.03      6826821.48
      1427004.98      6826937.99
#Sta/Elev= 30
  4495.7 2268.16  4554.1 2263.06  4575.1 2255.98  4596.1 2257.19    4611 2252.95
    4617 2255.09  4625.9 2251.46    4632  2253.4  4646.9 2244.01    4653 2248.05
  4661.9 2242.74  4667.9 2246.68  4676.8 2242.89  4682.8 2244.29  4689.2 2240.65
  4703.8 2238.46  4785.4 2239.66  4883.5 2234.35  4978.8 2234.91  4991.5 2234.06
  4998.8 2230.82  4999.3 2228.35  4999.8 2227.85    5013 2228.35  5021.4 2232.89
  5057.8 2234.79  5086.5 2244.81  5136.5 2252.94  5172.9 2256.81  5216.9 2257.66
#Mann= 5 ,-1 , 0
  4495.7     .07       0  4785.4     .16       0  4978.8     .07       0
  4999.3     .07       0    5013     .07       0
Bank Sta=4999.3,5013
XS Rating Curve= 0 ,0
Exp/Cntr=0.3,0.1

Type RM Length L Ch R = 1 ,2450    ,497,497,497
BEGIN DESCRIPTION:
Bitter Creek Trib8T3 3.0
END DESCRIPTION:
XS GIS Cut Line= 3
      1426255.01      6826738.02      1426449.03      6827085.65
        1426655.      6827487.99
#Sta/Elev= 30
  4601.9 2267.52  4615.6 2264.57    4691 2254.05  4734.4 2244.37  4744.6 2243.76
  4756.1 2242.24  4772.1 2237.79  4793.8 2234.47  4830.9 2230.85  4961.8 2230.65
  4970.8 2223.58  4971.3 2223.08  4984.7 2223.58  4991.2 2229.76  5088.4 2236.74
  5128.9 2244.94  5148.7 2247.91  5171.2 2248.06  5182.9  2249.5  5249.8 2249.74
  5272.3 2253.13  5282.7 2253.11  5304.9 2258.58  5310.5 2258.98  5317.2 2261.46
  5332.7  2263.4  5377.1 2263.33  5384.6 2265.18  5393.7 2269.57    5452 2277.19
#Mann= 5 ,-1 , 0
  4601.9     .07       0  4744.6     .16       0  4970.8     .07       0
  4984.7     .16       0  5128.9     .07       0
Bank Sta=4970.8,4984.7
XS Rating Curve= 0 ,0
Exp/Cntr=0.3,0.1

Type RM Length L Ch R = 1 ,1953    ,498,498,498
BEGIN DESCRIPTION:
Bitter Creek Trib8T3 2.0
END DESCRIPTION:
XS GIS Cut Line= 3
        1426005.      6826838.02      1425988.43      6827171.11
        1426005.      6827538.03
#Sta/Elev= 30
  4666.5 2259.53  4676.5 2258.02  4686.5 2255.02    4702 2247.91  4736.6 2233.51
  4764.3 2226.83  4796.6 2225.38  4856.7 2226.18  4866.7 2227.32  4903.4 2226.58
  4986.9 2226.97  4995.9 2224.76    5000 2224.76    5010 2219.77  5010.5 2219.27
  5023.9 2219.77  5026.9 2223.21  5033.4 2225.82  5038.4 2224.33  5046.9 2226.42
    5087 2230.02    5117 2229.24    5147 2233.95  5237.1 2238.18  5277.2 2244.63
  5297.2 2252.31  5327.2  2259.1  5337.2 2262.38  5347.2 2264.39  5367.3 2265.04
#Mann= 5 ,-1 , 0
  4666.5     .07       0    4702     .16       0  4903.4     .07       0
    5010     .07       0  5023.9     .07       0
Bank Sta=5010,5023.9
XS Rating Curve= 0 ,0
Exp/Cntr=0.3,0.1

Type RM Length L Ch R = 1 ,1455    ,500,500,500
BEGIN DESCRIPTION:
Bitter Creek Trib8T3 1.0
END DESCRIPTION:
XS GIS Cut Line= 3
        1425655.        6826788.      1425538.34      6827020.46
      1425805.02      6827588.03
#Sta/Elev= 30
  4739.9 2253.25  4753.9 2251.22    4807 2238.34  4820.9 2236.63  4851.8 2227.94
  4865.5 2226.11  4918.9 2223.19    4994 2222.08  5003.4 2218.59  5008.9 2221.98
  5012.4 2217.04  5012.9 2216.54  5026.4 2217.04  5031.7 2217.15  5041.5 2221.57
  5052.1 2222.36  5077.3 2223.97  5085.7 2222.34  5117.4 2223.69    5152 2221.23
  5185.1 2223.37  5317.7 2222.65  5439.2 2230.19  5470.5 2233.54  5498.9 2240.14
  5516.1 2251.68  5538.7 2258.21  5572.8 2260.11  5595.6 2264.63  5627.1 2266.12
#Mann= 4 ,-1 , 0
  4739.9     .16       0  5012.4     .07       0  5026.4     .16       0
  5052.1     .07       0
Bank Sta=5012.4,5026.4
XS Rating Curve= 0 ,0
Exp/Cntr=0.3,0.1

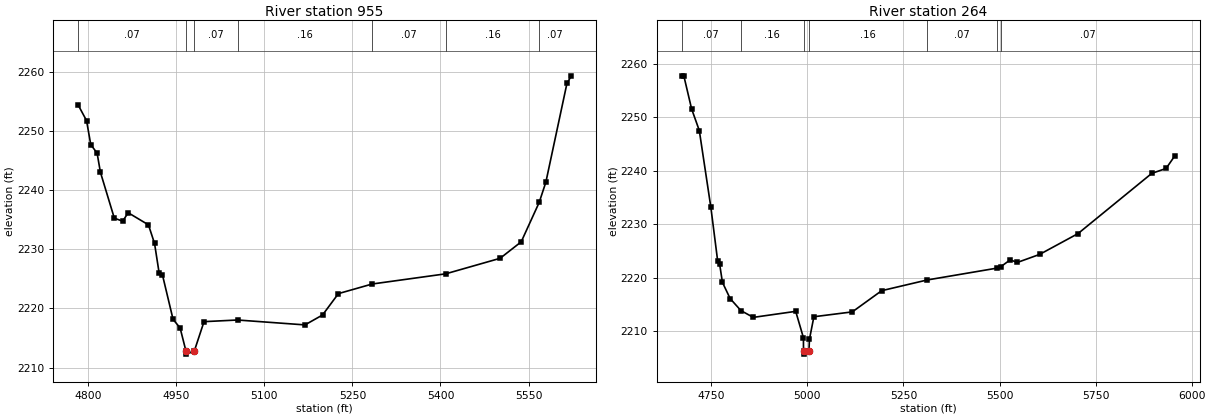
Type RM Length L Ch R = 1 ,955     ,691,691,691
BEGIN DESCRIPTION:
Bitter Creek Trib8T3 0.1
END DESCRIPTION:
XS GIS Cut Line= 3
      1425054.98      6826987.96      1425139.94      6827187.86
        1425655.        6827538.
#Sta/Elev= 30
  4782.8 2254.53  4797.4 2251.83  4804.6 2247.76  4815.4 2246.31    4821 2243.09
  4844.7  2235.3  4858.9 2234.79  4868.3 2236.22  4902.8 2234.17  4913.2 2231.01
  4921.1 2225.94  4926.5 2225.75  4944.7 2218.16  4956.7 2216.71  4966.7 2212.77
  4967.2 2212.27  4980.8 2212.77  4997.4 2217.77  5054.5 2218.05  5169.3 2217.22
  5199.2  2218.9  5226.2 2222.52  5283.8 2224.15  5408.8 2225.87  5501.5  2228.5
  5537.4 2231.29    5568 2237.96  5579.4  2241.4  5615.3 2258.13  5622.8 2259.41
#Mann= 7 ,-1 , 0
  4782.8     .07       0  4966.7     .07       0  4980.8     .07       0
  5054.5     .16       0  5283.8     .07       0  5408.8     .16       0
    5568     .07       0
Bank Sta=4966.7,4980.8
XS Rating Curve= 0 ,0
Exp/Cntr=0.3,0.1

Type RM Length L Ch R = 1 ,264     ,0,0,0
BEGIN DESCRIPTION:
Bitter Creek Trib8T3 4313
END DESCRIPTION:
XS GIS Cut Line= 3
       1424601.6      6827261.88      1424630.08      6827588.24
      1425510.27      6827962.34
#Sta/Elev= 30
  4672.4 2257.77  4678.5 2257.75  4698.6  2251.6  4718.7 2247.53  4748.8 2233.15
  4766.4 2223.16  4771.5 2222.58  4778.9  2219.1    4799 2216.06  4827.1 2213.81
  4859.2 2212.54  4969.6 2213.67  4989.7 2208.73  4989.9 2206.16  4990.4 2205.66
    5004 2206.16  5005.4 2208.46  5016.9 2212.66  5116.9 2213.57  5193.3 2217.54
  5311.4 2219.54  5493.1 2221.76  5502.6 2221.99  5527.9 2223.32  5546.1 2222.82
  5604.3 2224.33  5704.3 2228.23  5896.3 2239.51  5933.4 2240.42  5956.4 2242.81
#Mann= 7 ,-1 , 0
  4672.4     .07       0  4827.1     .16       0  4989.9     .07       0
    5004     .16       0  5311.4     .07       0  5493.1     .16       0
  5502.6     .07       0
Bank Sta=4989.9,5004
XS Rating Curve= 0 ,0
Exp/Cntr=0.3,0.1

Chan Stop Cuts=-1
Use User Specified Reach Order=0
Composite Channel Slope=5