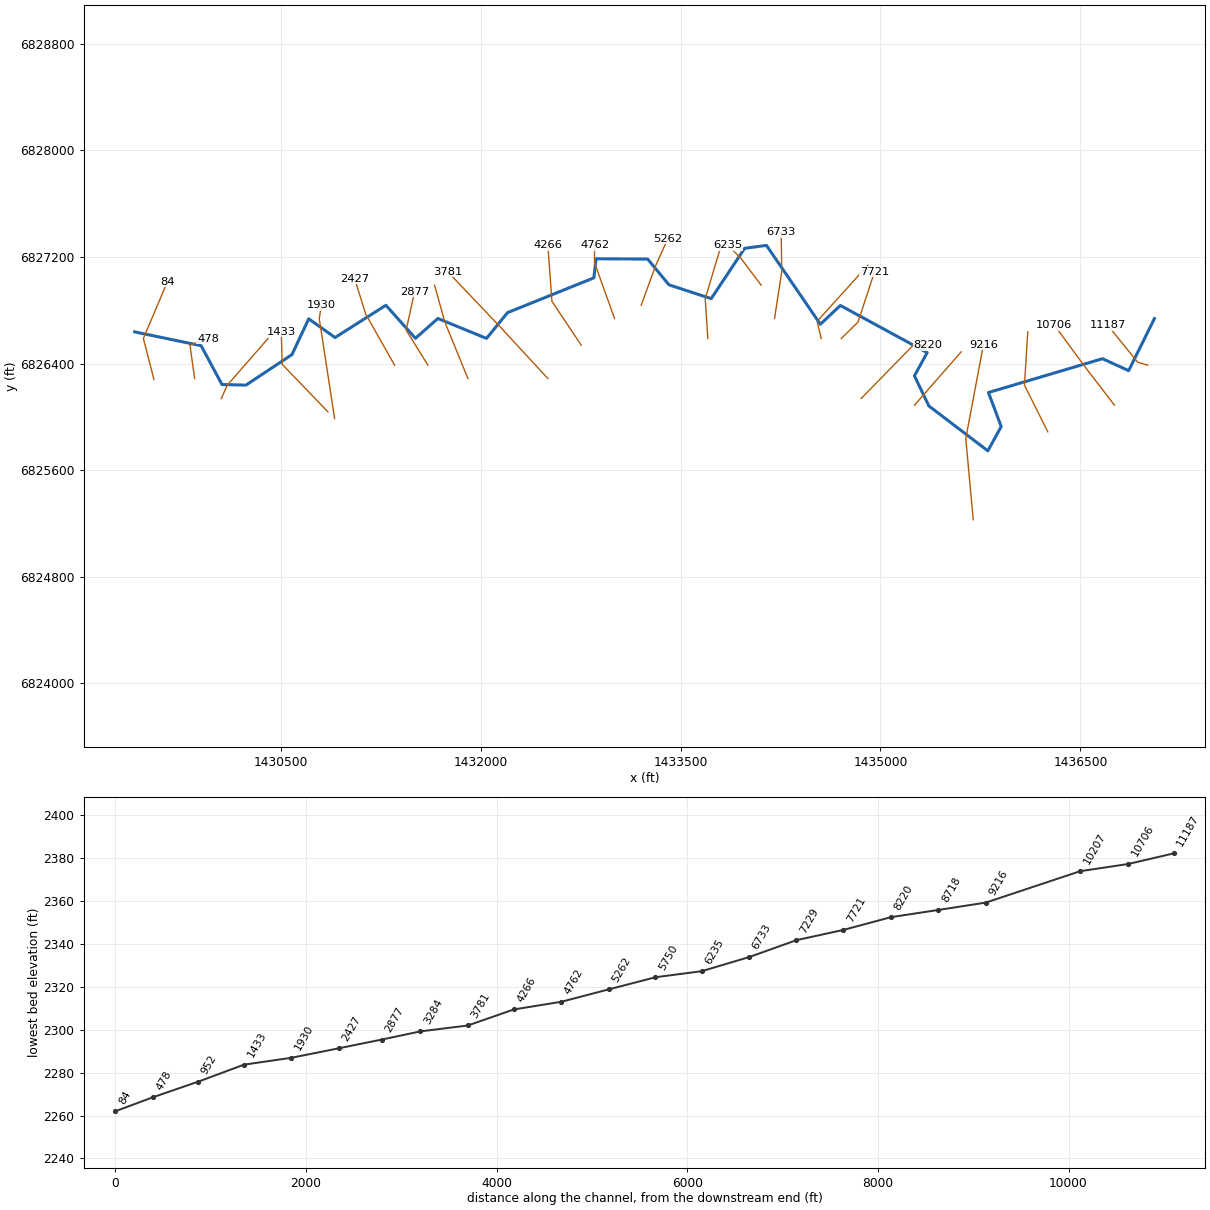
--- Bitter Creek Trib8T3_1.prj (project) ---

Proj Title=Bitter Creek Trib8T3_1 Base Level Engineering
Current Plan=p01
Default Exp/Contr=0.3,0.1
English Units
Geom File=g01
Flow File=f01
Plan File=p01
BEGIN DESCRIPTION:
Bitter Creek Trib8T3_1
END DESCRIPTION:

--- Bitter Creek Trib8T3_1.p01 (plan) ---

Plan Title=Multiple Run
Short Identifier=Multiple
Geom File=g01
Flow File=f01
Subcritical Flow
K Sum by GR= 0
Std Step Tol= 0.01
Critical Tol= 0.01
Num of Std Step Trials= 20
Max Error Tol= 0.3
Flow Tol Ratio= 0.001
Split Flow NTrial= 30
Split Flow Tol= 0.02
Split Flow Ratio= 0.02
Log Output Level= 0
Friction Slope Method= 1
Unsteady Friction Slope Method= 2
Unsteady Bridges Friction Slope Method= 1
Parabolic Critical Depth
Global Vel Dist=  1 , 1 , 1
Global Log Level= 0
CheckData=True
Encroach Param= -1, 0, 0, 0
BEGIN DESCRIPTION:
Multiple Run
END DESCRIPTION:

--- Bitter Creek Trib8T3_1.f01 (steady flow) ---

Flow Title=Multiple
Number of Profiles=7
Profile Names=10-year,25-year,50-year,1pct_min,100-year,1pct_plu,500-year
River Rch & RM= Bitter Creek Tri,Reach-1,11187
     369     534     675     426     850    1695    1360
River Rch & RM= Bitter Creek Tri,Reach-1,10706
     547     804    1028     653    1304    2601    2123
River Rch & RM= Bitter Creek Tri,Reach-1,4762
     627     924    1185     754    1505    3003    2459
Boundary for River Rch & Prof#=Bitter Creek Tri,Reach-1,1
Up Type=0
Dn Type=3
Dn Slope=0.005
Boundary for River Rch & Prof#=Bitter Creek Tri,Reach-1,2
Up Type=0
Dn Type=3
Dn Slope=0.005
Boundary for River Rch & Prof#=Bitter Creek Tri,Reach-1,3
Up Type=0
Dn Type=3
Dn Slope=0.005
Boundary for River Rch & Prof#=Bitter Creek Tri,Reach-1,4
Up Type=0
Dn Type=3
Dn Slope=0.005
Boundary for River Rch & Prof#=Bitter Creek Tri,Reach-1,5
Up Type=0
Dn Type=3
Dn Slope=0.005
Boundary for River Rch & Prof#=Bitter Creek Tri,Reach-1,6
Up Type=0
Dn Type=3
Dn Slope=0.005
Boundary for River Rch & Prof#=Bitter Creek Tri,Reach-1,7
Up Type=0
Dn Type=3
Dn Slope=0.005

--- Bitter Creek Trib8T3_1.g01 (geometry) ---

Geom Title=Existing Conditions

River Reach=Bitter Creek Tri,Reach-1
Reach XY= 30
      1437055.00      6826738.00      1436861.67      6826346.96
      1436665.55      6826436.90      1435809.59      6826182.83
      1435905.78      6825927.95      1435805.30      6825745.20
      1435363.14      6826081.94      1435254.63      6826308.20
      1435350.27      6826482.41      1434698.86      6826836.27
      1434548.97      6826695.18      1434144.71      6827287.03
      1433980.97      6827265.35      1433730.13      6826887.46
      1433413.31      6826991.08      1433253.54      6827184.46
      1432866.49      6827186.51      1432849.81      6827043.45
      1432202.33      6826782.58      1432044.57      6826589.04
      1431679.92      6826738.63      1431511.09      6826589.57
      1431289.92      6826837.82      1430908.15      6826595.51
      1430710.71      6826736.12      1430585.37      6826467.84
      1430239.80      6826238.50      1430060.08      6826243.03
      1429903.55      6826534.47      1429405.00      6826638.00

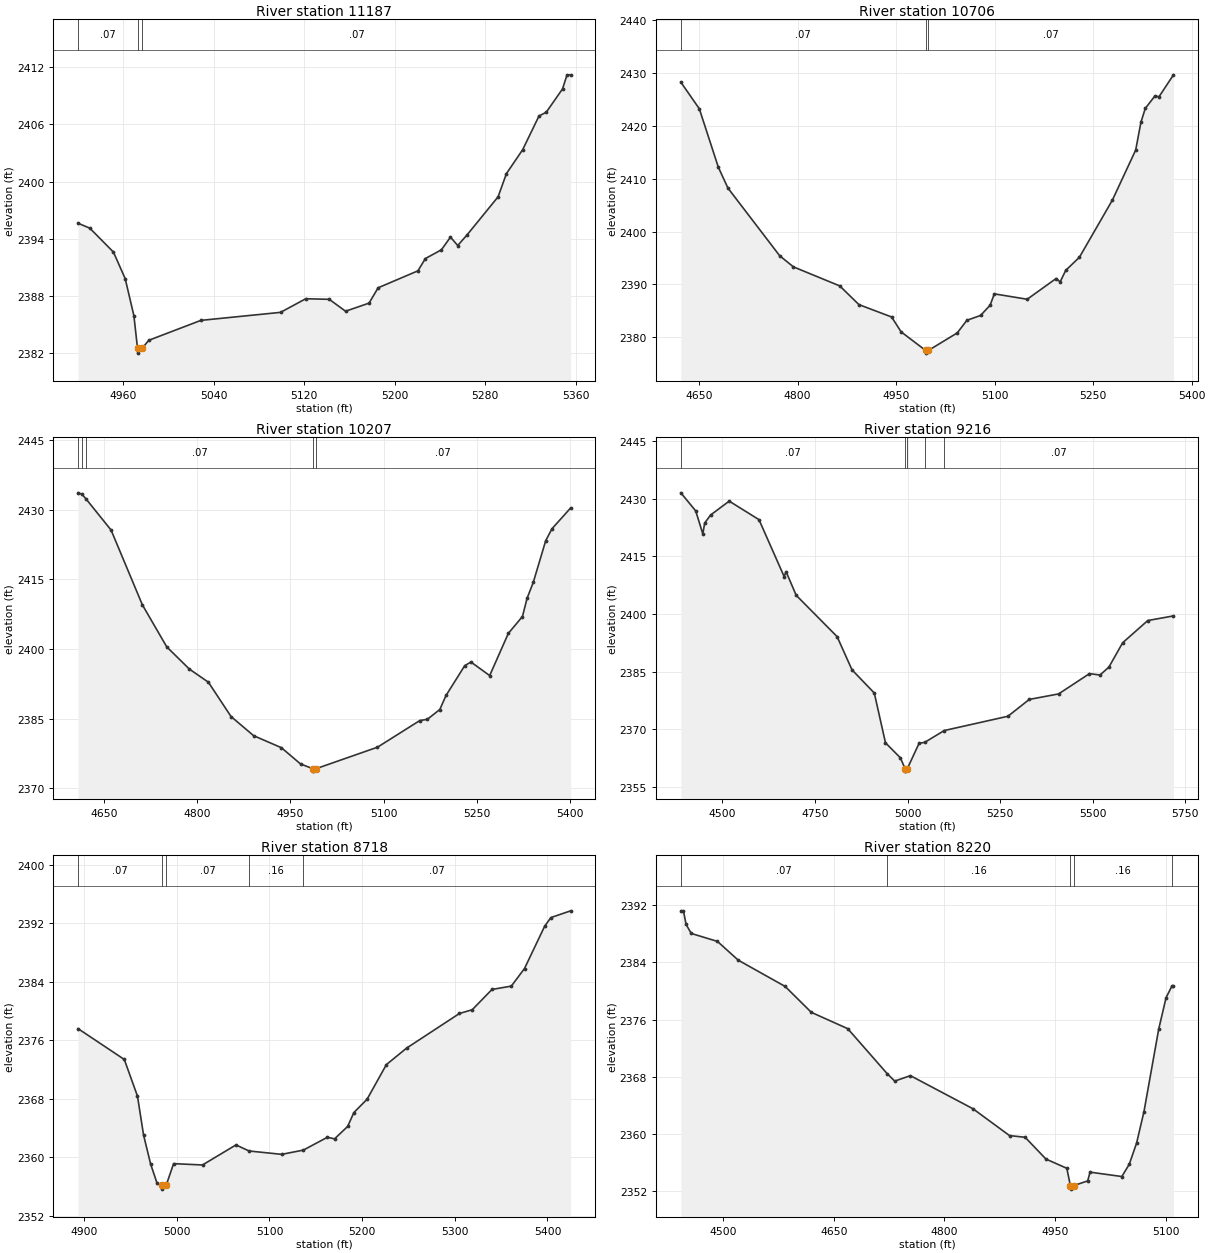
Type RM Length L Ch R = 1,11187,481,481,481
BEGIN DESCRIPTION:
Bitter Creek Trib8T3_1 21.0
END DESCRIPTION:
XS GIS Cut Line= 3
      1437004.96      6826388.01      1436928.39      6826411.18
      1436705.01      6826687.99
#Sta/Elev= 30
  4920.0 2395.63  4930.4 2395.11  4951.3 2392.60  4961.7 2389.81  4969.4 2385.92
  4972.6 2382.49  4972.8 2381.99  4976.6 2382.49  4982.6 2383.34  5028.7 2385.43
  5099.1 2386.27  5121.4 2387.70  5142.2 2387.64  5156.6 2386.39  5177.4 2387.24
  5185.4 2388.85  5220.6 2390.63  5227.2 2391.92  5241.4 2392.84  5249.4 2394.17
  5255.8 2393.29  5263.7 2394.35  5291.5 2398.40  5298.9 2400.84  5313.3 2403.36
  5327.7 2406.89  5334.1 2407.28  5348.5 2409.73  5352.5 2411.21  5355.7 2411.21
#Mann=3,-1,0
  4920.0    0.07       0  4972.6    0.07       0  4976.6    0.07       0
Bank Sta=4972.6,4976.6
Exp/Cntr=0.3,0.1

Type RM Length L Ch R = 1,10706,499,499,499
BEGIN DESCRIPTION:
Bitter Creek Trib8T3_1 20.0
END DESCRIPTION:
XS GIS Cut Line= 3
      1436755.02      6826087.98      1436525.10      6826387.76
      1436304.99      6826688.02
#Sta/Elev= 30
  4622.2 2428.23  4650.3 2423.21  4679.3 2412.15  4693.9 2408.22  4772.7 2395.43
  4793.6 2393.33  4864.2 2389.73  4893.3 2386.20  4943.1 2383.86  4957.6 2381.05
  4995.0 2377.53  4995.3 2377.03  4999.0 2377.53  5043.1 2380.85  5057.7 2383.23
  5078.6 2384.15  5093.2 2386.10  5099.5 2388.23  5149.6 2387.21  5193.6 2391.13
  5199.8 2390.50  5208.2 2392.66  5229.1 2395.15  5279.3 2405.95  5314.8 2415.41
  5322.7 2420.63  5329.4 2423.28  5344.1 2425.63  5350.3 2425.48  5372.3 2429.62
#Mann=3,-1,0
  4622.2    0.07       0  4995.0    0.07       0  4999.0    0.07       0
Bank Sta=4995,4999
Exp/Cntr=0.3,0.1

Type RM Length L Ch R = 1,10207,991,991,991
BEGIN DESCRIPTION:
Bitter Creek Trib8T3_1 19.0
END DESCRIPTION:
XS GIS Cut Line= 3
      1436255.00      6825888.00      1436079.93      6826238.18
      1436105.00      6826637.99
#Sta/Elev= 30
  4608.5 2433.60  4614.7 2433.31  4620.9 2432.36  4661.6 2425.59  4711.9 2409.51
  4751.1 2400.46  4787.4 2395.69  4818.1 2392.85  4854.5 2385.47  4890.8 2381.35
  4935.5 2378.76  4966.3 2375.26  4986.6 2374.22  4986.8 2373.72  4990.7 2374.22
  5090.0 2378.87  5158.0 2384.60  5170.2 2384.87  5190.2 2386.98  5200.2 2390.00
  5230.3 2396.42  5240.3 2397.19  5270.4 2394.28  5300.4 2403.36  5323.1 2406.99
  5330.5 2410.90  5340.5 2414.34  5360.5 2423.31  5370.6 2425.88  5400.6 2430.35
#Mann=5,-1,0
  4608.5    0.07       0  4614.7    0.16       0  4620.9    0.07       0
  4986.6    0.07       0  4990.7    0.07       0
Bank Sta=4986.6,4990.7
Exp/Cntr=0.3,0.1

Type RM Length L Ch R = 1,9216,498,498,498
BEGIN DESCRIPTION:
Bitter Creek Trib8T3_1 18.0
END DESCRIPTION:
XS GIS Cut Line= 3
      1435695.81      6825228.02      1435639.72      6825837.35
      1435772.51      6826542.76
#Sta/Elev= 30
  4388.1 2431.52  4428.2 2426.82  4447.4 2420.83  4452.4 2423.65  4468.4 2425.75
  4518.6 2429.36  4599.0 2424.54  4667.0 2409.71  4672.0 2411.03  4699.4 2404.86
  4809.9 2394.10  4850.0 2385.47  4910.3 2379.42  4940.4 2366.48  4980.6 2362.57
  4994.0 2359.60  4994.3 2359.10  4998.7 2359.60  5031.2 2366.35  5046.5 2366.59
  5099.0 2369.66  5271.0 2373.38  5328.6 2377.76  5407.7 2379.19  5491.1 2384.47
  5519.6 2384.11  5543.6 2386.18  5580.7 2392.51  5648.5 2398.29  5717.8 2399.49
#Mann=5,-1,0
  4388.1    0.07       0  4994.0    0.07       0  4998.7    0.07       0
  5046.5    0.16       0  5099.0    0.07       0
Bank Sta=4994,4998.7
Exp/Cntr=0.3,0.1

Type RM Length L Ch R = 1,8718,498,498,498
BEGIN DESCRIPTION:
Bitter Creek Trib8T3_1 17.0
END DESCRIPTION:
XS GIS Cut Line= 3
      1435254.98      6826087.97      1435325.17      6826168.07
      1435604.97      6826487.97
#Sta/Elev= 30
  4893.5 2377.59  4943.4 2373.38  4957.6 2368.38  4964.2 2363.05  4971.8 2359.10
  4978.5 2356.57  4983.7 2356.17  4984.0 2355.67  4988.5 2356.17  4996.6 2359.15
  5027.8 2358.97  5063.9 2361.71  5078.0 2360.88  5113.2 2360.42  5136.6 2361.00
  5162.6 2362.76  5170.2 2362.53  5184.4 2364.23  5191.1 2366.13  5205.3 2367.94
  5226.2 2372.68  5248.0 2374.93  5305.0 2379.66  5318.8 2380.17  5340.1 2382.94
  5361.0 2383.40  5375.2 2385.80  5397.0 2391.59  5403.7 2392.76  5425.0 2393.68
#Mann=5,-1,0
  4893.5    0.07       0  4983.7    0.07       0  4988.5    0.07       0
  5078.0    0.16       0  5136.6    0.07       0
Bank Sta=4983.7,4988.5
Exp/Cntr=0.3,0.1

Type RM Length L Ch R = 1,8220,499,499,499
BEGIN DESCRIPTION:
Bitter Creek Trib8T3_1 16.0
END DESCRIPTION:
XS GIS Cut Line= 3
      1434854.97      6826137.96      1435244.37      6826536.65
      1435354.96      6826538.00
#Sta/Elev= 30
  4442.7 2391.18  4446.2 2391.18  4449.8 2389.28  4456.8 2388.02  4492.3 2386.91
  4520.5 2384.29  4584.1 2380.62  4619.6 2377.00  4669.0 2374.72  4722.4 2368.44
  4732.7 2367.40  4753.9 2368.16  4838.7 2363.54  4888.3 2359.79  4909.5 2359.55
  4937.7 2356.51  4966.0 2355.22  4970.8 2352.81  4971.1 2352.31  4975.6 2352.81
  4994.3 2353.46  4997.5 2354.68  5040.6 2354.07  5050.6 2355.77  5060.6 2358.74
  5070.6 2363.13  5090.6 2374.66  5100.6 2379.06  5108.3 2380.63  5110.6 2380.63
#Mann=5,-1,0
  4442.7    0.07       0  4722.4    0.16       0  4970.8    0.07       0
  4975.6    0.16       0  5108.3    0.07       0
Bank Sta=4970.8,4975.6
Exp/Cntr=0.3,0.1

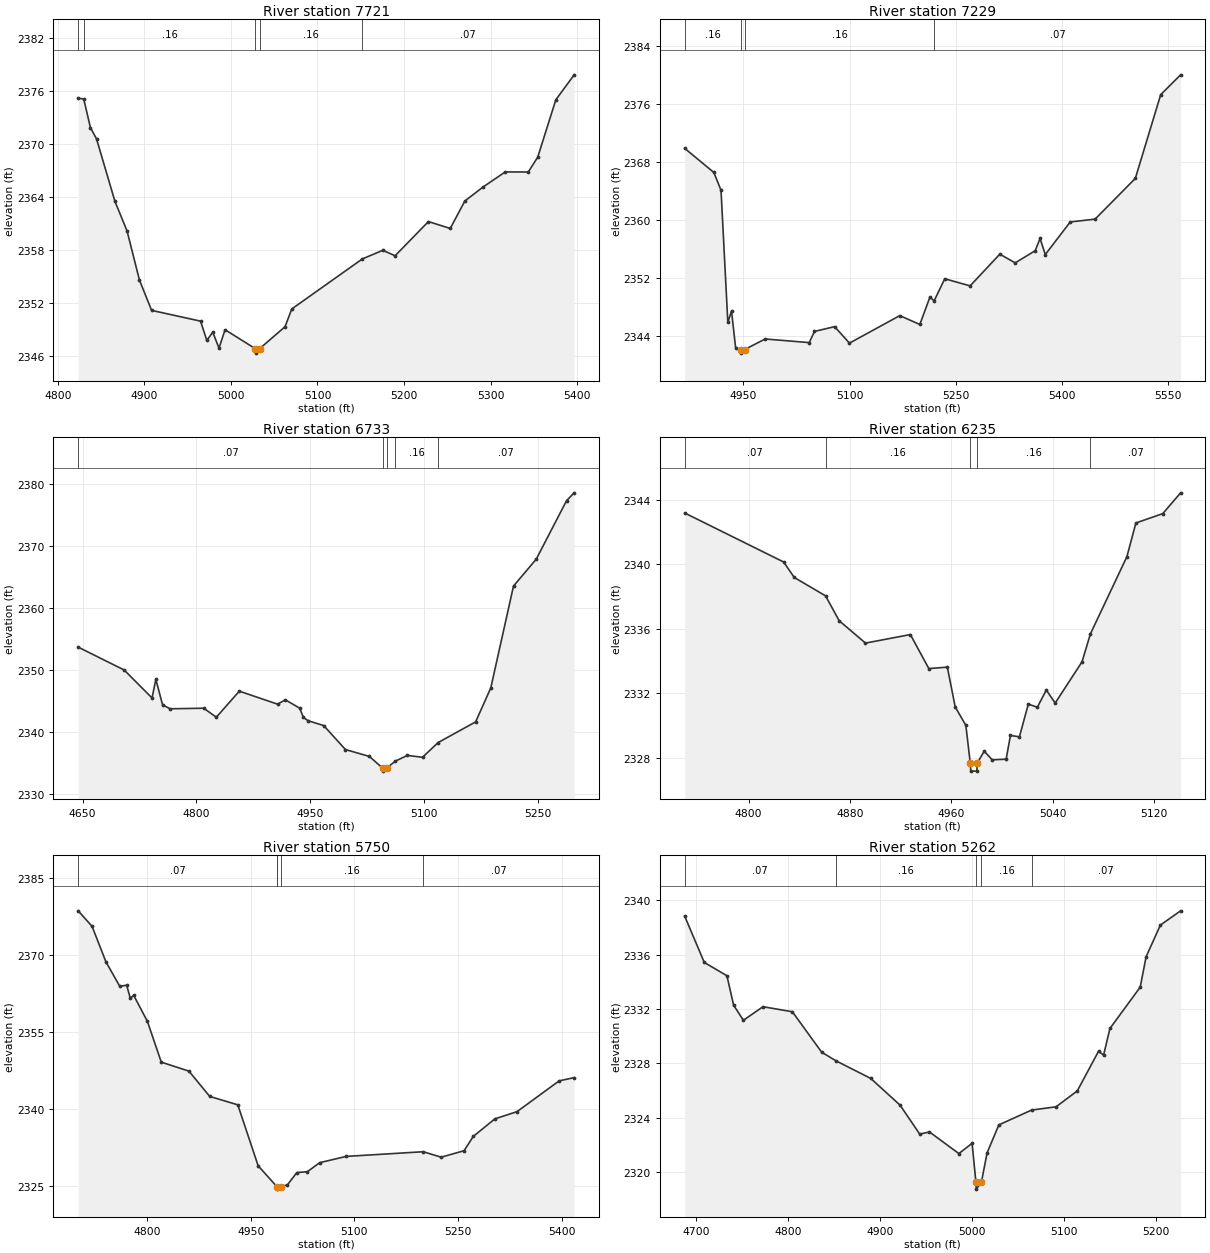
Type RM Length L Ch R = 1,7721,492,492,492
BEGIN DESCRIPTION:
Bitter Creek Trib8T3_1 15.0
END DESCRIPTION:
XS GIS Cut Line= 3
      1434704.98      6826587.98      1434831.32      6826711.23
      1434955.01      6827088.04
#Sta/Elev= 30
  4823.5 2375.23  4829.9 2375.13  4837.6 2371.90  4844.7 2370.61  4865.9 2363.56
  4880.0 2360.18  4894.2 2354.66  4908.3 2351.21  4964.9 2349.99  4972.1 2347.81
  4979.0 2348.74  4986.2 2346.93  4993.2 2349.02  5028.2 2346.87  5028.5 2346.37
  5033.1 2346.87  5062.5 2349.36  5070.3 2351.37  5151.8 2357.03  5175.5 2358.01
  5189.7 2357.39  5228.2 2361.26  5253.4 2360.48  5270.3 2363.59  5291.3 2365.17
  5317.0 2366.88  5343.6 2366.87  5354.5 2368.55  5375.4 2375.04  5396.6 2377.87
#Mann=5,-1,0
  4823.5    0.07       0  4829.9    0.16       0  5028.2    0.07       0
  5033.1    0.16       0  5151.8    0.07       0
Bank Sta=5028.2,5033.1
Exp/Cntr=0.3,0.1

Type RM Length L Ch R = 1,7229,496,496,496
BEGIN DESCRIPTION:
Bitter Creek Trib8T3_1 14.0
END DESCRIPTION:
XS GIS Cut Line= 3
      1434554.99      6826588.03      1434524.57      6826717.20
      1434905.02      6827138.02
#Sta/Elev= 30
  4867.3 2369.84  4908.4 2366.52  4918.6 2364.06  4928.2 2345.85  4933.4 2347.42
  4939.2 2342.35  4947.0 2342.11  4947.4 2341.61  4952.0 2342.11  4980.9 2343.56
  5043.1 2343.06  5050.5 2344.60  5078.9 2345.26  5099.9 2342.99  5170.9 2346.78
  5199.2 2345.56  5213.4 2349.32  5219.4 2348.82  5234.4 2351.86  5270.2 2350.88
  5312.1 2355.25  5333.8 2354.05  5362.1 2355.73  5368.9 2357.42  5376.3 2355.20
  5411.5 2359.69  5446.6 2360.08  5503.4 2365.70  5539.2 2377.24  5567.3 2379.97
#Mann=4,-1,0
  4867.3    0.16       0  4947.0    0.07       0  4952.0    0.16       0
  5219.4    0.07       0
Bank Sta=4947,4952
Exp/Cntr=0.3,0.1

Type RM Length L Ch R = 1,6733,498,498,498
BEGIN DESCRIPTION:
Bitter Creek Trib8T3_1 13.0
END DESCRIPTION:
XS GIS Cut Line= 3
      1434205.00      6826737.97      1434259.16      6827089.72
      1434255.00      6827387.99
#Sta/Elev= 30
  4644.1 2353.71  4704.8 2350.02  4741.5 2345.52  4746.5 2348.53  4755.4 2344.40
  4765.5 2343.78  4809.7 2343.87  4826.3 2342.42  4856.6 2346.62  4907.2 2344.52
  4917.3 2345.23  4936.2 2343.88  4941.2 2342.38  4947.7 2341.84  4967.9 2341.08
  4996.6 2337.22  5028.3 2336.10  5045.5 2334.24  5046.0 2333.74  5051.0 2334.24
  5062.6 2335.36  5078.3 2336.27  5098.3 2335.97  5118.7 2338.33  5168.3 2341.67
  5188.3 2347.12  5218.3 2363.55  5248.3 2367.88  5288.3 2377.30  5298.3 2378.56
#Mann=5,-1,0
  4644.1    0.07       0  5045.5    0.07       0  5051.0    0.07       0
  5062.6    0.16       0  5118.7    0.07       0
Bank Sta=5045.5,5051
Exp/Cntr=0.3,0.1

Type RM Length L Ch R = 1,6235,485,485,485
BEGIN DESCRIPTION:
Bitter Creek Trib8T3_1 12.0
END DESCRIPTION:
XS GIS Cut Line= 3
      1434105.02      6826987.97      1433954.63      6827188.18
      1433855.02      6827287.98
#Sta/Elev= 30
  4749.6 2343.18  4827.7 2340.14  4836.1 2339.18  4860.8 2338.04  4871.5 2336.50
  4892.3 2335.11  4927.7 2335.64  4942.3 2333.53  4956.9 2333.62  4963.1 2331.15
  4971.5 2330.01  4975.0 2327.67  4975.4 2327.17  4980.1 2327.17  4980.5 2327.67
  4986.0 2328.41  4992.3 2327.87  5003.3 2327.91  5006.7 2329.38  5013.8 2329.30
  5020.8 2331.33  5027.9 2331.13  5035.0 2332.20  5042.0 2331.39  5063.2 2333.95
  5069.8 2335.68  5098.6 2340.47  5105.7 2342.56  5126.9 2343.14  5141.0 2344.43
#Mann=5,-1,0
  4749.6    0.07       0  4860.8    0.16       0  4975.0    0.07       0
  4980.5    0.16       0  5069.8    0.07       0
Bank Sta=4975,4980.5
Exp/Cntr=0.3,0.1

Type RM Length L Ch R = 1,5750,488,488,488
BEGIN DESCRIPTION:
Bitter Creek Trib8T3_1 11.0
END DESCRIPTION:
XS GIS Cut Line= 3
      1433705.00      6826587.99      1433685.15      6826887.23
      1433805.00      6827287.99
#Sta/Elev= 30
  4700.1 2378.53  4720.2 2375.50  4740.2 2368.61  4760.2 2363.85  4770.3 2364.04
  4775.5 2361.52  4780.5 2362.07  4800.3 2357.01  4820.4 2349.07  4860.5 2347.32
  4890.5 2342.40  4931.2 2340.76  4960.7 2328.89  4987.3 2324.91  4988.0 2324.85
  4988.4 2324.35  4993.6 2324.85  5003.0 2325.17  5016.7 2327.57  5032.1 2327.75
  5049.8 2329.50  5088.1 2330.72  5199.7 2331.63  5225.8 2330.57  5258.9 2331.83
  5272.2 2334.61  5303.5 2338.03  5335.5 2339.43  5396.5 2345.42  5418.3 2346.06
#Mann=5,-1,0
  4700.1    0.07       0  4987.3    0.16       0  4988.0    0.07       0
  4993.6    0.16       0  5199.7    0.07       0
Bank Sta=4988,4993.6
Exp/Cntr=0.3,0.1

Type RM Length L Ch R = 1,5262,500,500,500
BEGIN DESCRIPTION:
Bitter Creek Trib8T3_1 10.0
END DESCRIPTION:
XS GIS Cut Line= 3
      1433205.01      6826838.02      1433311.76      6827131.51
      1433405.01      6827338.03
#Sta/Elev= 30
  4687.7 2338.83  4709.0 2335.42  4733.6 2334.44  4740.9 2332.27  4751.5 2331.16
  4772.8 2332.16  4804.7 2331.79  4836.6 2328.81  4852.0 2328.18  4889.9 2326.88
  4921.8 2324.91  4943.1 2322.78  4953.7 2322.94  4985.6 2321.35  5000.0 2322.10
  5004.2 2319.23  5004.6 2318.73  5010.1 2319.23  5016.3 2321.40  5029.1 2323.46
  5064.6 2324.55  5091.2 2324.79  5114.3 2325.96  5137.4 2328.88  5142.9 2328.60
  5149.8 2330.56  5182.7 2333.60  5189.1 2335.84  5204.6 2338.17  5226.6 2339.22
#Mann=5,-1,0
  4687.7    0.07       0  4852.0    0.16       0  5004.2    0.07       0
  5010.1    0.16       0  5064.6    0.07       0
Bank Sta=5004.2,5010.1
Exp/Cntr=0.3,0.1

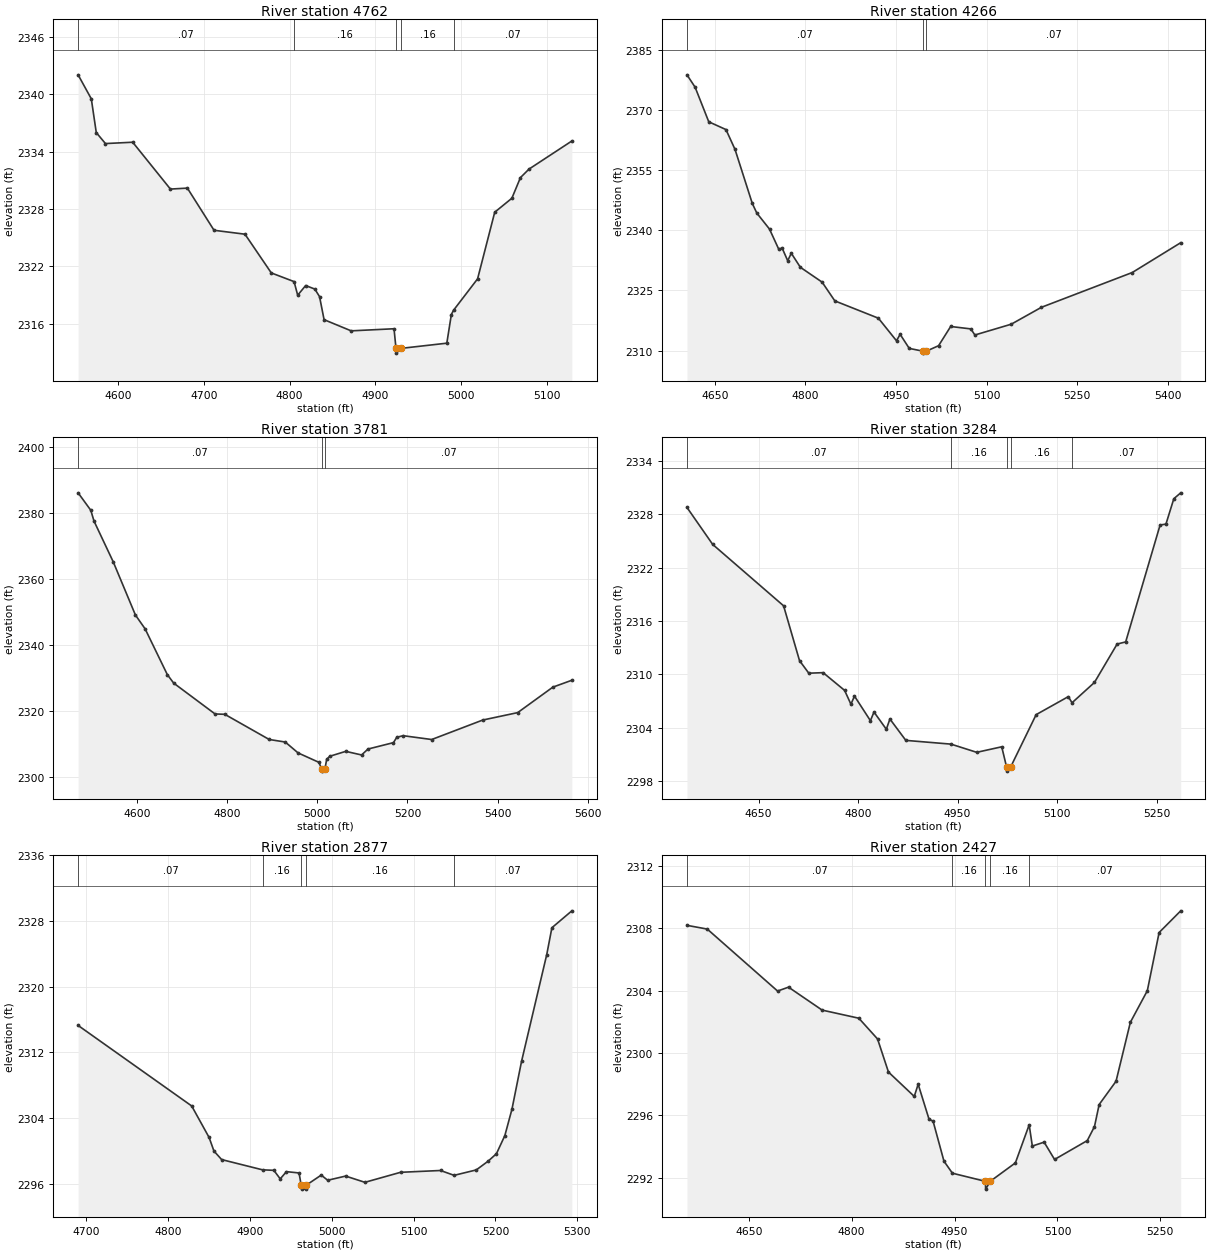
Type RM Length L Ch R = 1,4762,496,496,496
BEGIN DESCRIPTION:
Bitter Creek Trib8T3_1 9.0
END DESCRIPTION:
XS GIS Cut Line= 3
      1433005.00      6826738.01      1432854.43      6827158.57
      1432855.00      6827287.97
#Sta/Elev= 30
  4553.3 2342.04  4568.7 2339.53  4574.5 2336.00  4585.2 2334.85  4617.0 2334.99
  4661.0 2330.09  4680.8 2330.19  4711.9 2325.78  4748.0 2325.37  4778.7 2321.32
  4805.3 2320.41  4809.5 2318.99  4818.8 2320.00  4829.5 2319.63  4835.0 2318.84
  4840.3 2316.43  4871.9 2315.26  4921.9 2315.48  4924.2 2313.43  4924.7 2312.93
  4930.4 2313.43  4983.5 2313.97  4988.8 2316.97  4991.3 2317.41  5019.4 2320.70
  5039.4 2327.67  5059.4 2329.13  5069.4 2331.29  5079.4 2332.18  5129.4 2335.12
#Mann=5,-1,0
  4553.3    0.07       0  4805.3    0.16       0  4924.2    0.07       0
  4930.4    0.16       0  4991.3    0.07       0
Bank Sta=4924.2,4930.4
Exp/Cntr=0.3,0.1

Type RM Length L Ch R = 1,4266,485,485,485
BEGIN DESCRIPTION:
Bitter Creek Trib8T3_1 8.0
END DESCRIPTION:
XS GIS Cut Line= 3
      1432755.01      6826537.98      1432535.17      6826867.59
      1432505.00      6827288.01
#Sta/Elev= 30
  4603.8 2378.76  4617.3 2375.67  4639.9 2367.05  4668.4 2365.11  4683.4 2360.16
  4712.0 2346.69  4719.5 2344.29  4740.5 2340.30  4755.5 2335.38  4761.6 2335.51
  4770.6 2332.42  4776.6 2334.27  4791.6 2330.78  4827.6 2327.08  4848.7 2322.40
  4920.8 2318.09  4950.8 2312.46  4956.8 2314.07  4971.9 2310.56  4994.1 2309.88
  4994.6 2309.38  5000.4 2309.88  5020.5 2311.23  5040.5 2316.02  5073.9 2315.42
  5080.6 2313.90  5140.8 2316.59  5190.9 2320.81  5341.3 2329.48  5421.5 2336.91
#Mann=3,-1,0
  4603.8    0.07       0  4994.1    0.07       0  5000.4    0.07       0
Bank Sta=4994.1,5000.4
Exp/Cntr=0.3,0.1

Type RM Length L Ch R = 1,3781,497,497,497
BEGIN DESCRIPTION:
Bitter Creek Trib8T3_1 7.0
END DESCRIPTION:
XS GIS Cut Line= 3
      1432504.99      6826288.01      1432144.22      6826678.32
      1431755.00      6827088.00
#Sta/Elev= 30
  4468.5 2386.08  4496.6 2380.82  4503.9 2377.51  4546.4 2365.24  4595.8 2349.12
  4617.3 2344.94  4666.7 2331.08  4680.8 2328.52  4772.7 2319.19  4794.2 2319.09
  4892.9 2311.47  4928.6 2310.70  4957.0 2307.41  5003.1 2304.57  5010.2 2302.40
  5010.7 2301.90  5016.5 2302.40  5020.5 2305.43  5027.3 2306.39  5062.9 2307.88
  5098.1 2306.79  5112.3 2308.58  5168.9 2310.52  5176.2 2312.13  5190.3 2312.62
  5253.8 2311.46  5367.1 2317.35  5444.8 2319.60  5522.8 2327.30  5565.1 2329.39
#Mann=3,-1,0
  4468.5    0.07       0  5010.2    0.07       0  5016.5    0.07       0
Bank Sta=5010.2,5016.5
Exp/Cntr=0.3,0.1

Type RM Length L Ch R = 1,3284,407,407,407
BEGIN DESCRIPTION:
Bitter Creek Trib8T3_1 6.0
END DESCRIPTION:
XS GIS Cut Line= 3
      1431905.01      6826287.97      1431731.81      6826711.96
      1431655.01      6826987.98
#Sta/Elev= 30
  4542.0 2328.74  4580.8 2324.59  4687.7 2317.70  4711.7 2311.55  4725.7 2310.14
  4747.3 2310.20  4779.7 2308.21  4789.2 2306.66  4794.6 2307.57  4818.6 2304.81
  4824.0 2305.78  4842.6 2303.85  4848.0 2305.00  4872.0 2302.60  4940.1 2302.18
  4978.9 2301.26  5016.6 2301.88  5023.8 2299.65  5024.3 2299.15  5030.3 2299.65
  5068.5 2305.49  5117.0 2307.51  5122.6 2306.82  5156.4 2309.10  5190.6 2313.41
  5203.5 2313.65  5255.4 2326.77  5264.2 2326.87  5276.1 2329.72  5286.5 2330.38
#Mann=5,-1,0
  4542.0    0.07       0  4940.1    0.16       0  5023.8    0.07       0
  5030.3    0.16       0  5122.6    0.07       0
Bank Sta=5023.8,5030.3
Exp/Cntr=0.3,0.1

Type RM Length L Ch R = 1,2877,450,450,450
BEGIN DESCRIPTION:
Bitter Creek Trib8T3_1 5.0
END DESCRIPTION:
XS GIS Cut Line= 3
      1431604.99      6826388.01      1431441.70      6826651.52
      1431505.00      6826938.01
#Sta/Elev= 30
  4690.0 2315.28  4828.8 2305.47  4850.1 2301.63  4856.0 2299.98  4865.4 2298.94
  4915.4 2297.69  4929.2 2297.63  4937.0 2296.59  4944.6 2297.47  4960.0 2297.31
  4962.6 2295.84  4963.1 2295.34  4968.6 2295.34  4969.1 2295.84  4987.1 2297.05
  4995.0 2296.42  5016.9 2296.93  5040.5 2296.17  5084.1 2297.39  5132.9 2297.61
  5149.5 2297.02  5176.6 2297.68  5191.0 2298.74  5201.2 2299.65  5211.5 2301.86
  5220.2 2305.08  5231.9 2310.90  5262.7 2323.91  5269.0 2327.18  5293.4 2329.24
#Mann=5,-1,0
  4690.0    0.07       0  4915.4    0.16       0  4962.6    0.07       0
  4969.1    0.16       0  5149.5    0.07       0
Bank Sta=4962.6,4969.1
Exp/Cntr=0.3,0.1

Type RM Length L Ch R = 1,2427,497,497,497
BEGIN DESCRIPTION:
Bitter Creek Trib8T3_1 4.0
END DESCRIPTION:
XS GIS Cut Line= 3
      1431354.98      6826388.03      1431138.45      6826771.06
      1431054.99      6827038.02
#Sta/Elev= 30
  4560.0 2308.18  4589.6 2307.94  4692.1 2303.97  4708.0 2304.22  4757.0 2302.75
  4810.5 2302.23  4837.8 2300.90  4853.7 2298.78  4891.3 2297.22  4897.0 2298.00
  4912.9 2295.75  4918.7 2295.64  4934.6 2293.07  4946.9 2292.30  4994.9 2291.78
  4995.4 2291.28  5002.0 2291.78  5038.7 2292.96  5058.8 2295.40  5063.4 2294.04
  5080.6 2294.29  5095.8 2293.18  5143.5 2294.39  5154.0 2295.29  5160.8 2296.70
  5185.4 2298.19  5206.3 2301.97  5231.0 2303.99  5248.2 2307.72  5279.7 2309.11
#Mann=5,-1,0
  4560.0    0.07       0  4946.9    0.16       0  4994.9    0.07       0
  5002.0    0.16       0  5058.8    0.07       0
Bank Sta=4994.9,5002
Exp/Cntr=0.3,0.1

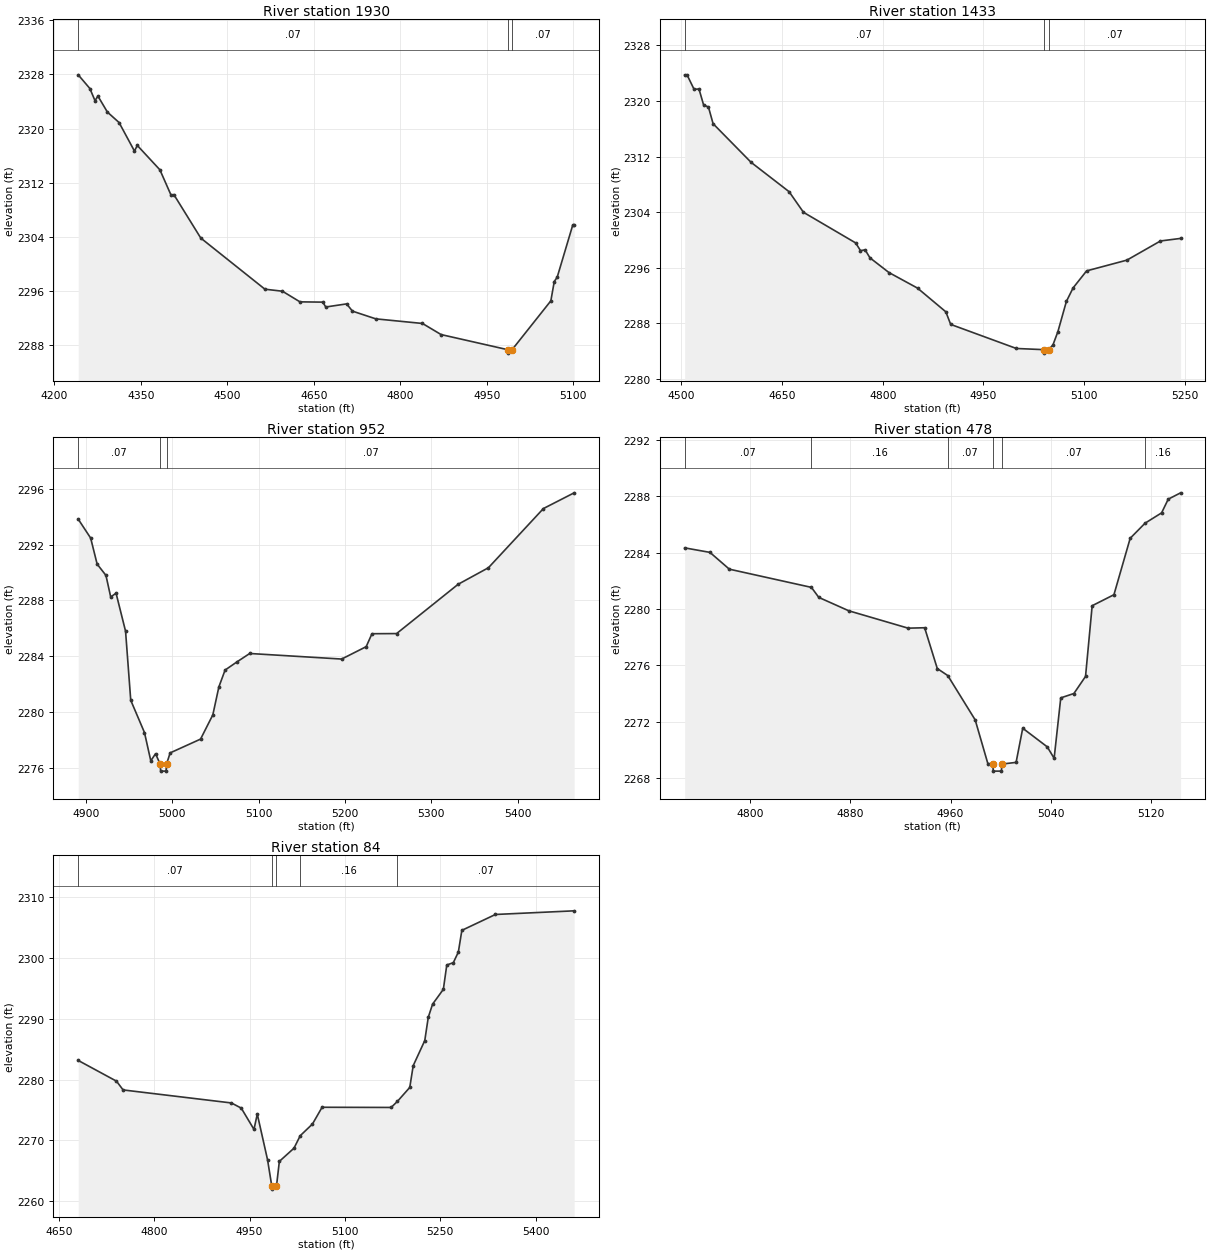
Type RM Length L Ch R = 1,1930,497,497,497
BEGIN DESCRIPTION:
Bitter Creek Trib8T3_1 3.0
END DESCRIPTION:
XS GIS Cut Line= 3
      1430905.00      6825988.00      1430789.90      6826737.82
      1430805.00      6826837.99
#Sta/Elev= 30
  4241.4 2327.95  4261.6 2325.93  4270.5 2324.14  4275.6 2324.81  4292.0 2322.45
  4312.2 2320.91  4338.9 2316.70  4343.9 2317.52  4383.0 2313.93  4402.2 2310.22
  4407.3 2310.26  4453.9 2303.85  4565.1 2296.30  4595.5 2296.00  4625.9 2294.43
  4665.5 2294.39  4670.6 2293.67  4706.8 2294.13  4716.9 2293.06  4757.4 2291.92
  4838.3 2291.24  4870.6 2289.60  4986.5 2287.36  4987.0 2286.86  4993.6 2287.36
  5060.9 2294.58  5066.8 2297.43  5071.9 2298.07  5098.8 2305.75  5101.3 2305.75
#Mann=3,-1,0
  4241.4    0.07       0  4986.5    0.07       0  4993.6    0.07       0
Bank Sta=4986.5,4993.6
Exp/Cntr=0.3,0.1

Type RM Length L Ch R = 1,1433,481,481,481
BEGIN DESCRIPTION:
Bitter Creek Trib8T3_1 2.0
END DESCRIPTION:
XS GIS Cut Line= 3
      1430855.02      6826037.98      1430511.76      6826394.49
      1430505.00      6826637.99
#Sta/Elev= 30
  4505.1 2323.77  4508.6 2323.77  4519.1 2321.68  4526.4 2321.73  4533.3 2319.42
  4540.5 2319.13  4547.4 2316.73  4604.0 2311.16  4660.6 2306.93  4682.0 2303.96
  4759.7 2299.55  4766.9 2298.44  4773.8 2298.55  4781.0 2297.40  4809.3 2295.28
  4851.8 2293.04  4894.0 2289.62  4901.2 2287.81  4999.0 2284.34  5039.9 2284.17
  5040.4 2283.67  5047.1 2284.17  5053.5 2284.85  5060.9 2286.78  5073.5 2291.12
  5083.5 2293.07  5103.6 2295.52  5163.6 2297.07  5213.6 2299.83  5243.6 2300.20
#Mann=3,-1,0
  4505.1    0.07       0  5039.9    0.07       0  5047.1    0.07       0
Bank Sta=5039.9,5047.1
Exp/Cntr=0.3,0.1

Type RM Length L Ch R = 1,952,474,474,474
BEGIN DESCRIPTION:
Bitter Creek Trib8T3_1 1.0
END DESCRIPTION:
XS GIS Cut Line= 3
      1430054.99      6826137.97      1430099.34      6826237.32
      1430405.00      6826588.00
#Sta/Elev= 30
  4891.2 2293.84  4905.6 2292.48  4913.1 2290.61  4923.3 2289.80  4928.8 2288.25
  4935.0 2288.52  4946.0 2285.79  4952.0 2280.83  4967.9 2278.51  4975.2 2276.48
  4980.7 2276.99  4986.1 2276.24  4986.6 2275.74  4992.9 2275.74  4993.4 2276.24
  4997.6 2277.05  5032.8 2278.04  5047.0 2279.78  5054.0 2281.79  5061.2 2283.00
  5075.5 2283.61  5089.7 2284.19  5196.1 2283.79  5224.5 2284.68  5231.2 2285.61
  5259.7 2285.62  5330.9 2289.16  5366.0 2290.35  5429.6 2294.60  5465.2 2295.73
#Mann=3,-1,0
  4891.2    0.07       0  4986.1    0.07       0  4993.4    0.07       0
Bank Sta=4986.1,4993.4
Exp/Cntr=0.3,0.1

Type RM Length L Ch R = 1,478,394,394,394
BEGIN DESCRIPTION:
Bitter Creek Trib8T3_1 0.2
END DESCRIPTION:
XS GIS Cut Line= 3
      1429854.99      6826288.04      1429820.04      6826538.11
      1429955.01      6826588.01
#Sta/Elev= 30
  4747.5 2284.33  4767.7 2284.01  4783.2 2282.82  4848.8 2281.53  4854.7 2280.82
  4878.7 2279.87  4926.1 2278.64  4939.3 2278.67  4949.4 2275.78  4957.8 2275.28
  4979.7 2272.14  4989.8 2269.05  4993.7 2269.01  4994.2 2268.51  5000.6 2268.51
  5001.1 2269.01  5012.4 2269.13  5017.7 2271.55  5037.3 2270.23  5042.8 2269.42
  5048.1 2273.70  5058.6 2274.01  5067.9 2275.22  5073.2 2280.23  5090.6 2281.01
  5103.6 2285.01  5115.5 2286.08  5128.7 2286.81  5134.0 2287.78  5143.9 2288.23
#Mann=6,-1,0
  4747.5    0.07       0  4848.8    0.16       0  4957.8    0.07       0
  4993.7    0.07       0  5001.1    0.07       0  5115.5    0.16       0
Bank Sta=4993.7,5001.1
Exp/Cntr=0.3,0.1

Type RM Length L Ch R = 1,84,0,0,0
BEGIN DESCRIPTION:
Bitter Creek Trib8T3_1 0.1
END DESCRIPTION:
XS GIS Cut Line= 3
      1429550.08      6826279.66      1429470.40      6826588.96
      1429650.03      6827012.98
#Sta/Elev= 30
  4680.6 2283.15  4740.8 2279.74  4751.2 2278.30  4921.5 2276.16  4937.0 2275.31
  4957.0 2271.81  4962.2 2274.33  4978.4 2266.79  4985.0 2262.49  4985.5 2261.99
  4992.4 2262.49  4996.9 2266.55  5019.9 2268.72  5029.7 2270.77  5049.0 2272.70
  5064.1 2275.45  5172.7 2275.42  5182.5 2276.41  5202.0 2278.71  5207.4 2282.29
  5225.6 2286.42  5231.1 2290.25  5237.9 2292.41  5254.8 2294.84  5260.2 2298.84
  5270.5 2299.23  5278.4 2300.97  5283.9 2304.54  5336.7 2307.15  5460.5 2307.75
#Mann=5,-1,0
  4680.6    0.07       0  4985.0    0.07       0  4992.4    0.07       0
  5029.7    0.16       0  5182.5    0.07       0
Bank Sta=4985,4992.4
Exp/Cntr=0.3,0.1

Chan Stop Cuts=-1