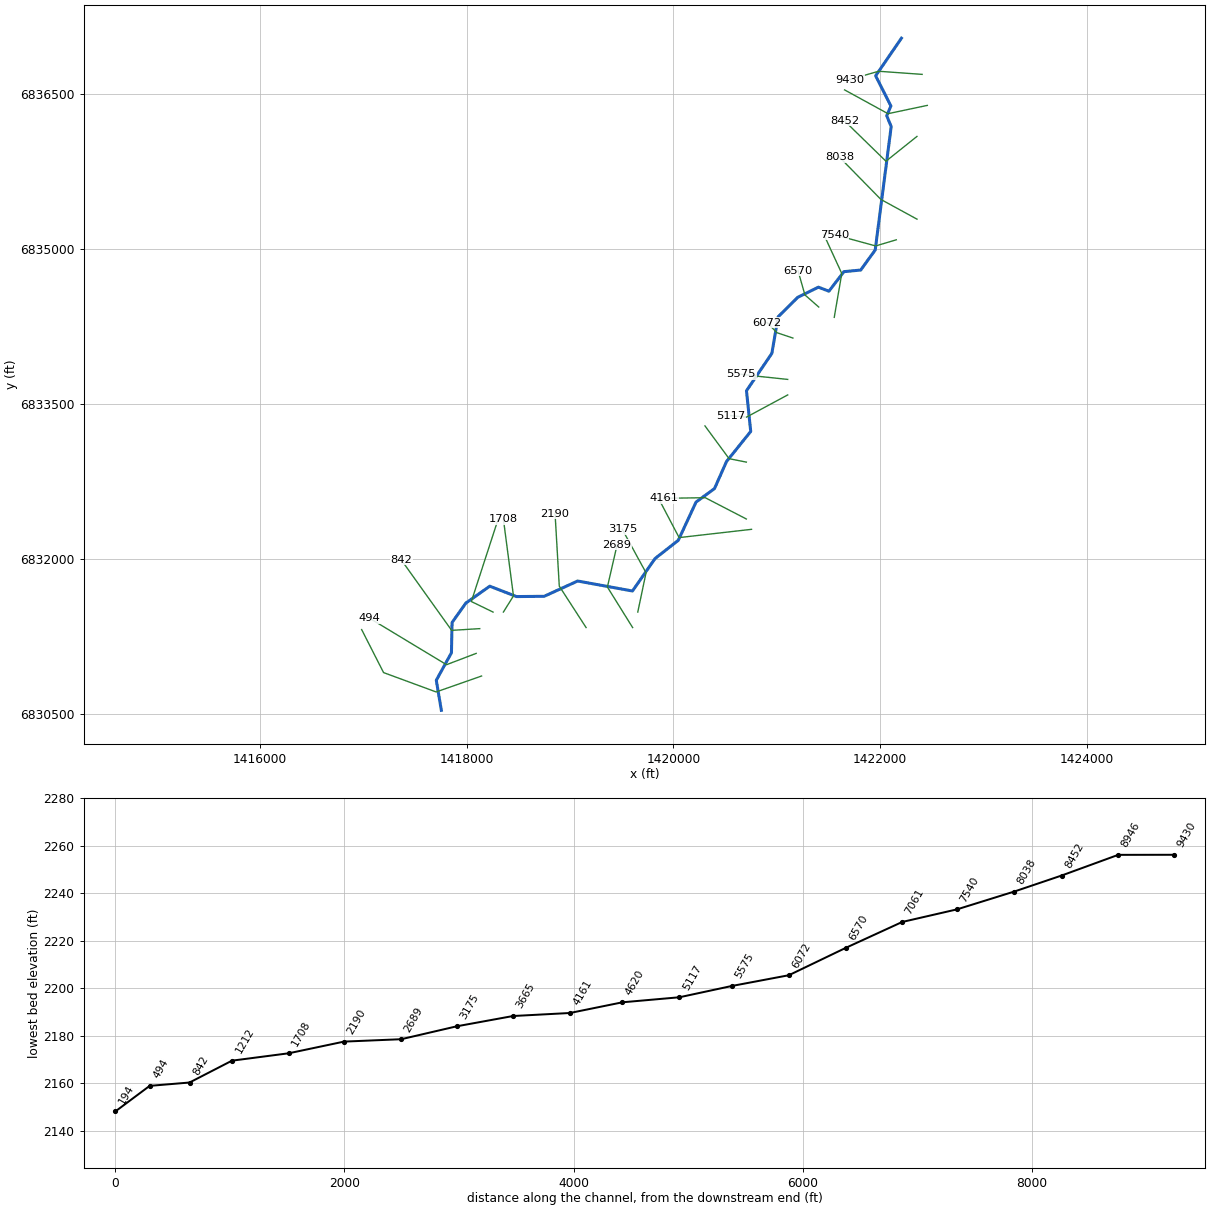
--- Bitter Creek Trib9.prj (project) ---

Proj Title=Bitter Creek Trib9 Base Level Engineering
Current Plan=p01
Default Exp/Contr=0.3,0.1
English Units
Geom File=g01
Flow File=f01
Plan File=p01
Y Axis Title=Elevation
X Axis Title(PF)=Main Channel Distance
X Axis Title(XS)=Station
BEGIN DESCRIPTION:
Bitter Creek Trib9
END DESCRIPTION:
DSS Export Rating Curves= 0
DSS Export Rating Curve Sorted= 0
DSS Export Volume Flow Curves= 0
DXF OffsetX= 0
DXF OffsetY= 0
DXF ScaleX= 1
DXF ScaleY= 10

--- Bitter Creek Trib9.p01 (plan) ---

Plan Title=Multiple Run
Short Identifier=Multiple
Geom File=g01
Flow File=f01
Subcritical Flow
K Sum by GR= 0
Std Step Tol= 0.01
Critical Tol= 0.01
Num of Std Step Trials= 20
Max Error Tol= 0.3
Flow Tol Ratio= 0.001
Split Flow NTrial= 30
Split Flow Tol= 0.02
Split Flow Ratio= 0.02
Log Output Level= 0
Friction Slope Method= 1
Unsteady Friction Slope Method= 2
Unsteady Bridges Friction Slope Method= 1
Parabolic Critical Depth
Global Vel Dist=  1 , 1 , 1
Global Log Level= 0
CheckData=True
Encroach Param= -1, 0, 0, 0
BEGIN DESCRIPTION:
Multiple Run
END DESCRIPTION:

--- Bitter Creek Trib9.f01 (steady flow) ---

Flow Title=Multiple
Program Version=4.10
Number of Profiles= 7
Profile Names=10-year,25-year,50-year,1pct_min,100-year,1pct_plu,500-year
River Rch & RM=Bitter Creek Tri,Reach-1         ,9430
     527     779    1000     638    1273    2541    2090
River Rch & RM=Bitter Creek Tri,Reach-1         ,2689
     557     823    1056     673    1343    2680    2203
Boundary for River Rch & Prof#=Bitter Creek Tri,Reach-1         , 1
Up Type= 0
Dn Type= 3
Dn Slope=0.035
Boundary for River Rch & Prof#=Bitter Creek Tri,Reach-1         , 2
Up Type= 0
Dn Type= 3
Dn Slope=0.035
Boundary for River Rch & Prof#=Bitter Creek Tri,Reach-1         , 3
Up Type= 0
Dn Type= 3
Dn Slope=0.035
Boundary for River Rch & Prof#=Bitter Creek Tri,Reach-1         , 4
Up Type= 0
Dn Type= 3
Dn Slope=0.035
Boundary for River Rch & Prof#=Bitter Creek Tri,Reach-1         , 5
Up Type= 0
Dn Type= 3
Dn Slope=0.035
Boundary for River Rch & Prof#=Bitter Creek Tri,Reach-1         , 6
Up Type= 0
Dn Type= 3
Dn Slope=0.035
Boundary for River Rch & Prof#=Bitter Creek Tri,Reach-1         , 7
Up Type= 0
Dn Type= 3
Dn Slope=0.035
DSS Import GetInterval= 0
DSS Import GetPeak= 0
DSS Import FillOption= 0

--- Bitter Creek Trib9.g01 (geometry) ---

Geom Title=Existing Conditions

River Reach=Bitter Creek Tri,Reach-1
Reach XY= 30
      1422205.00      6837038.00      1421955.40      6836674.09
      1422103.05      6836382.28      1422062.60      6836288.01
      1422105.78      6836183.44      1421951.24      6834989.56
      1421811.21      6834795.81      1421648.79      6834780.19
      1421503.57      6834591.07      1421401.69      6834629.93
      1421202.70      6834532.17      1421012.82      6834344.19
      1420951.45      6833989.47      1420706.25      6833628.30
      1420747.20      6833234.58      1420513.16      6832944.05
      1420396.87      6832681.93      1420218.47      6832551.57
      1420046.86      6832181.94      1419821.50      6832005.05
      1419603.55      6831691.53      1419073.43      6831788.18
      1418749.55      6831640.18      1418482.15      6831637.71
      1418223.28      6831738.07      1417991.76      6831574.38
      1417858.75      6831386.45      1417852.74      6831093.94
      1417706.21      6830828.41      1417755.00      6830538.00

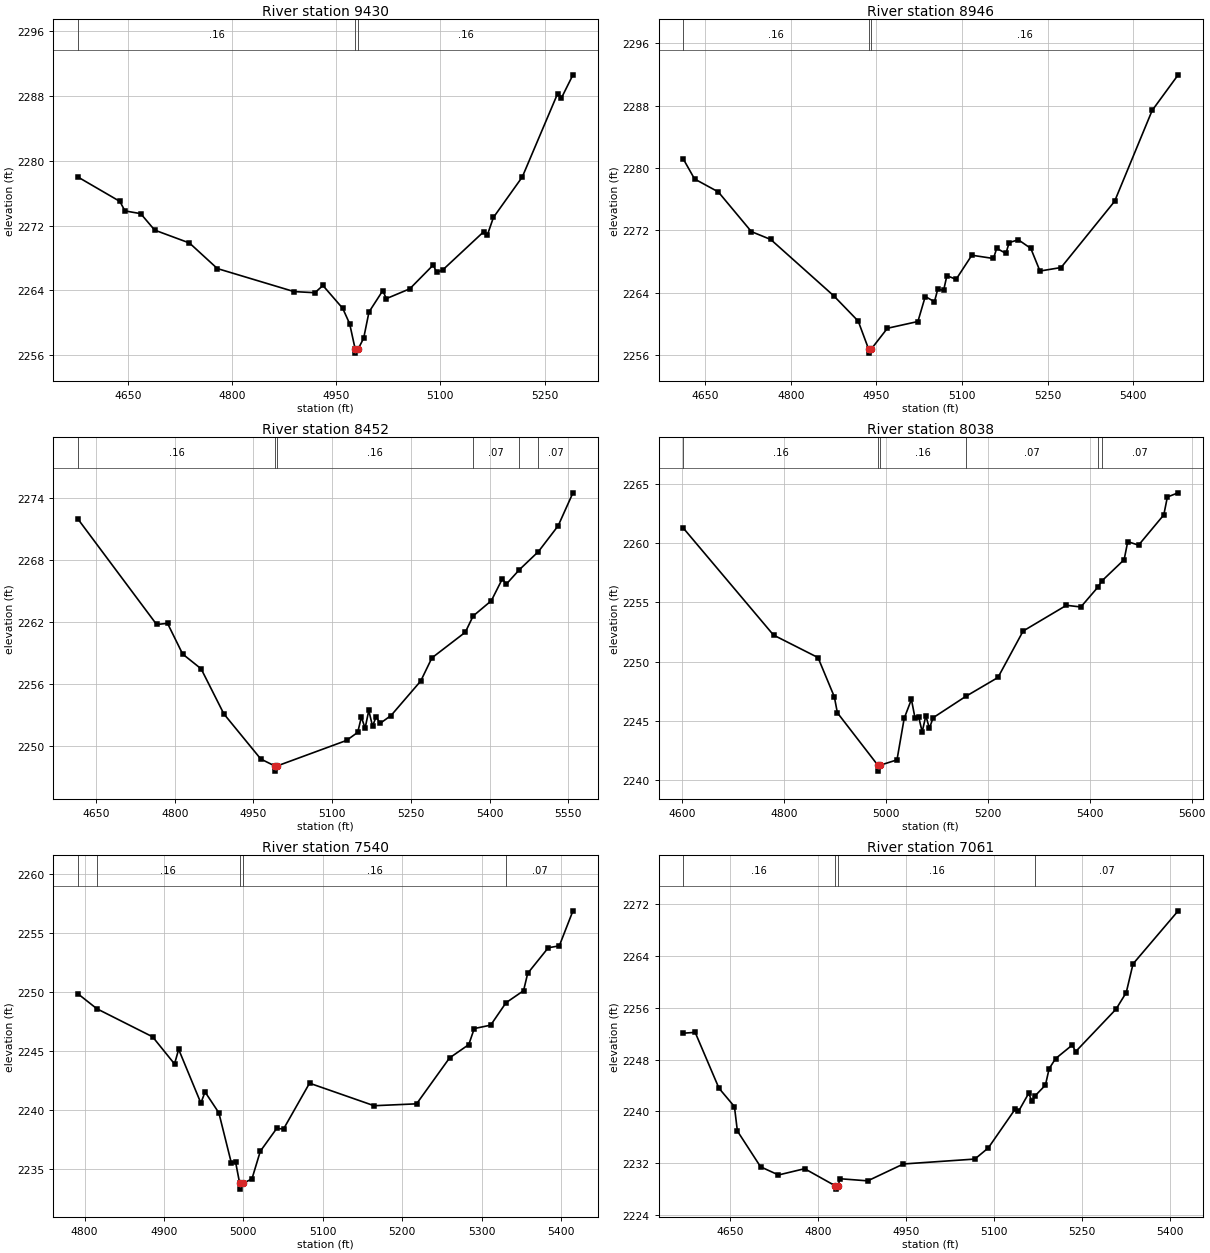
Type RM Length L Ch R = 1,9430,484,484,484
BEGIN DESCRIPTION:
Bitter Creek Trib9 17.0
END DESCRIPTION:
XS GIS Cut Line= 3
      1422405.01      6836688.00      1421984.50      6836718.20
      1421704.98      6836637.99
#Sta/Elev= 30
  4578.4 2277.98  4638.6 2274.98  4645.9 2273.81  4668.6 2273.47  4688.7 2271.44
  4738.8 2269.85  4778.9 2266.70  4889.2 2263.86  4919.3 2263.72  4930.9 2264.61
  4959.4 2261.79  4969.4 2259.89  4977.3 2256.77  4977.6 2256.27  4981.5 2256.77
  4989.5 2258.10  4997.2 2261.34  5017.0 2263.97  5022.2 2262.99  5055.9 2264.20
  5089.6 2267.13  5094.8 2266.22  5103.5 2266.54  5162.3 2271.24  5167.5 2270.81
  5176.3 2273.00  5217.9 2278.00  5268.7 2288.27  5273.9 2287.68  5290.8 2290.59
#Mann=3,-1,0
  4578.4    0.16       0  4977.3    0.07       0  4981.5    0.16       0
Bank Sta=4977.3,4981.5
Exp/Cntr=0.3,0.1

Type RM Length L Ch R = 1,8946,494,494,494
BEGIN DESCRIPTION:
Bitter Creek Trib9 16.0
END DESCRIPTION:
XS GIS Cut Line= 3
      1422455.03      6836388.01      1422074.89      6836307.87
      1421655.01      6836537.99
#Sta/Elev= 30
  4611.5 2281.17  4631.3 2278.60  4672.9 2276.94  4730.9 2271.84  4764.8 2270.83
  4875.2 2263.60  4918.1 2260.35  4936.4 2256.74  4936.7 2256.24  4940.7 2256.74
  4969.2 2259.43  5022.7 2260.30  5035.6 2263.51  5051.7 2262.84  5057.4 2264.43
  5067.8 2264.31  5073.5 2266.19  5089.6 2265.71  5117.2 2268.81  5155.1 2268.39
  5160.8 2269.70  5176.9 2269.04  5182.6 2270.43  5198.7 2270.79  5220.5 2269.69
  5236.6 2266.78  5273.6 2267.23  5367.4 2275.73  5433.2 2287.40  5478.8 2291.97
#Mann=3,-1,0
  4611.5    0.16       0  4936.4    0.07       0  4940.7    0.16       0
Bank Sta=4936.4,4940.7
Exp/Cntr=0.3,0.1

Type RM Length L Ch R = 1,8452,414,414,414
BEGIN DESCRIPTION:
Bitter Creek Trib9 15.0
END DESCRIPTION:
XS GIS Cut Line= 3
      1422355.03      6836088.02      1422055.05      6835847.98
      1421655.01      6836237.99
#Sta/Elev= 30
  4615.8 2271.91  4765.5 2261.72  4786.3 2261.83  4815.1 2258.86  4850.3 2257.43
  4893.6 2253.07  4964.0 2248.70  4990.7 2248.03  4991.0 2247.53  4995.0 2248.03
  5127.3 2250.50  5148.6 2251.28  5155.6 2252.76  5162.7 2251.68  5169.7 2253.40
  5176.9 2251.88  5183.9 2252.81  5191.0 2252.14  5212.1 2252.91  5268.7 2256.25
  5290.0 2258.49  5353.6 2260.97  5368.5 2262.54  5403.2 2264.02  5424.3 2266.15
  5431.5 2265.61  5456.8 2267.03  5493.0 2268.78  5530.5 2271.27  5558.7 2274.46
#Mann=6,-1,0
  4615.8    0.16       0  4990.7    0.07       0  4995.0    0.16       0
  5368.5    0.07       0  5456.8    0.16       0  5493.0    0.07       0
Bank Sta=4990.7,4995
Exp/Cntr=0.3,0.1

Type RM Length L Ch R = 1,8038,498,498,498
BEGIN DESCRIPTION:
Bitter Creek Trib9 14.0
END DESCRIPTION:
XS GIS Cut Line= 3
      1422355.02      6835287.99      1422006.49      6835478.29
      1421605.02      6835887.98
#Sta/Elev= 30
  4602.9 2261.28  4779.9 2252.25  4867.2 2250.35  4899.2 2247.04  4905.2 2245.69
  4984.5 2241.27  4984.8 2240.77  4989.1 2241.27  5022.1 2241.72  5036.2 2245.22
  5050.4 2246.82  5057.4 2245.26  5064.5 2245.37  5071.5 2244.08  5078.7 2245.44
  5085.7 2244.37  5092.8 2245.27  5156.8 2247.07  5220.1 2248.67  5269.5 2252.59
  5354.4 2254.76  5382.7 2254.62  5416.1 2256.29  5423.8 2256.81  5467.6 2258.61
  5474.7 2260.14  5495.8 2259.83  5545.4 2262.39  5552.4 2263.90  5573.6 2264.25
#Mann=6,-1,0
  4602.9    0.16       0  4984.5    0.07       0  4989.1    0.16       0
  5156.8    0.07       0  5416.1    0.16       0  5423.8    0.07       0
Bank Sta=4984.5,4989.1
Exp/Cntr=0.3,0.1

Type RM Length L Ch R = 1,7540,479,479,479
BEGIN DESCRIPTION:
Bitter Creek Trib9 13.0
END DESCRIPTION:
XS GIS Cut Line= 3
      1422154.99      6835088.00      1421955.40      6835028.74
      1421555.04      6835137.99
#Sta/Elev= 30
  4791.8 2249.84  4815.5 2248.58  4885.7 2246.20  4913.3 2243.90  4918.5 2245.14
  4946.5 2240.58  4951.7 2241.53  4969.1 2239.76  4984.9 2235.49  4990.1 2235.62
  4995.3 2233.79  4995.6 2233.29  4999.9 2233.79  5010.8 2234.16  5021.3 2236.50
  5041.9 2238.43  5050.6 2238.39  5083.3 2242.27  5164.6 2240.36  5218.1 2240.52
  5259.6 2244.41  5283.8 2245.54  5290.7 2246.90  5311.4 2247.19  5330.7 2249.09
  5352.8 2250.11  5358.0 2251.58  5383.9 2253.75  5397.8 2253.91  5415.0 2256.88
#Mann=5,-1,0
  4791.8    0.07       0  4815.5    0.16       0  4995.3    0.07       0
  4999.9    0.16       0  5330.7    0.07       0
Bank Sta=4995.3,4999.9
Exp/Cntr=0.3,0.1

Type RM Length L Ch R = 1,7061,491,491,491
BEGIN DESCRIPTION:
Bitter Creek Trib9 12.0
END DESCRIPTION:
XS GIS Cut Line= 3
      1421555.00      6834338.01      1421628.07      6834761.86
      1421455.02      6835137.96
#Sta/Elev= 30
  4569.9 2252.09  4590.2 2252.22  4630.8 2243.58  4657.2 2240.73  4662.2 2236.96
  4701.8 2231.42  4732.3 2230.16  4776.9 2231.13  4829.4 2228.47  4829.7 2227.97
  4834.1 2228.47  4836.8 2229.58  4884.5 2229.25  4945.3 2231.86  5067.2 2232.62
  5090.2 2234.35  5136.1 2240.36  5141.6 2239.99  5159.1 2242.80  5164.6 2241.53
  5169.7 2242.38  5187.6 2244.06  5193.9 2246.60  5204.9 2248.16  5233.5 2250.27
  5239.0 2249.23  5307.9 2255.80  5325.4 2258.37  5337.0 2262.81  5414.0 2271.02
#Mann=4,-1,0
  4569.9    0.16       0  4829.4    0.07       0  4834.1    0.16       0
  5169.7    0.07       0
Bank Sta=4829.4,4834.1
Exp/Cntr=0.3,0.1

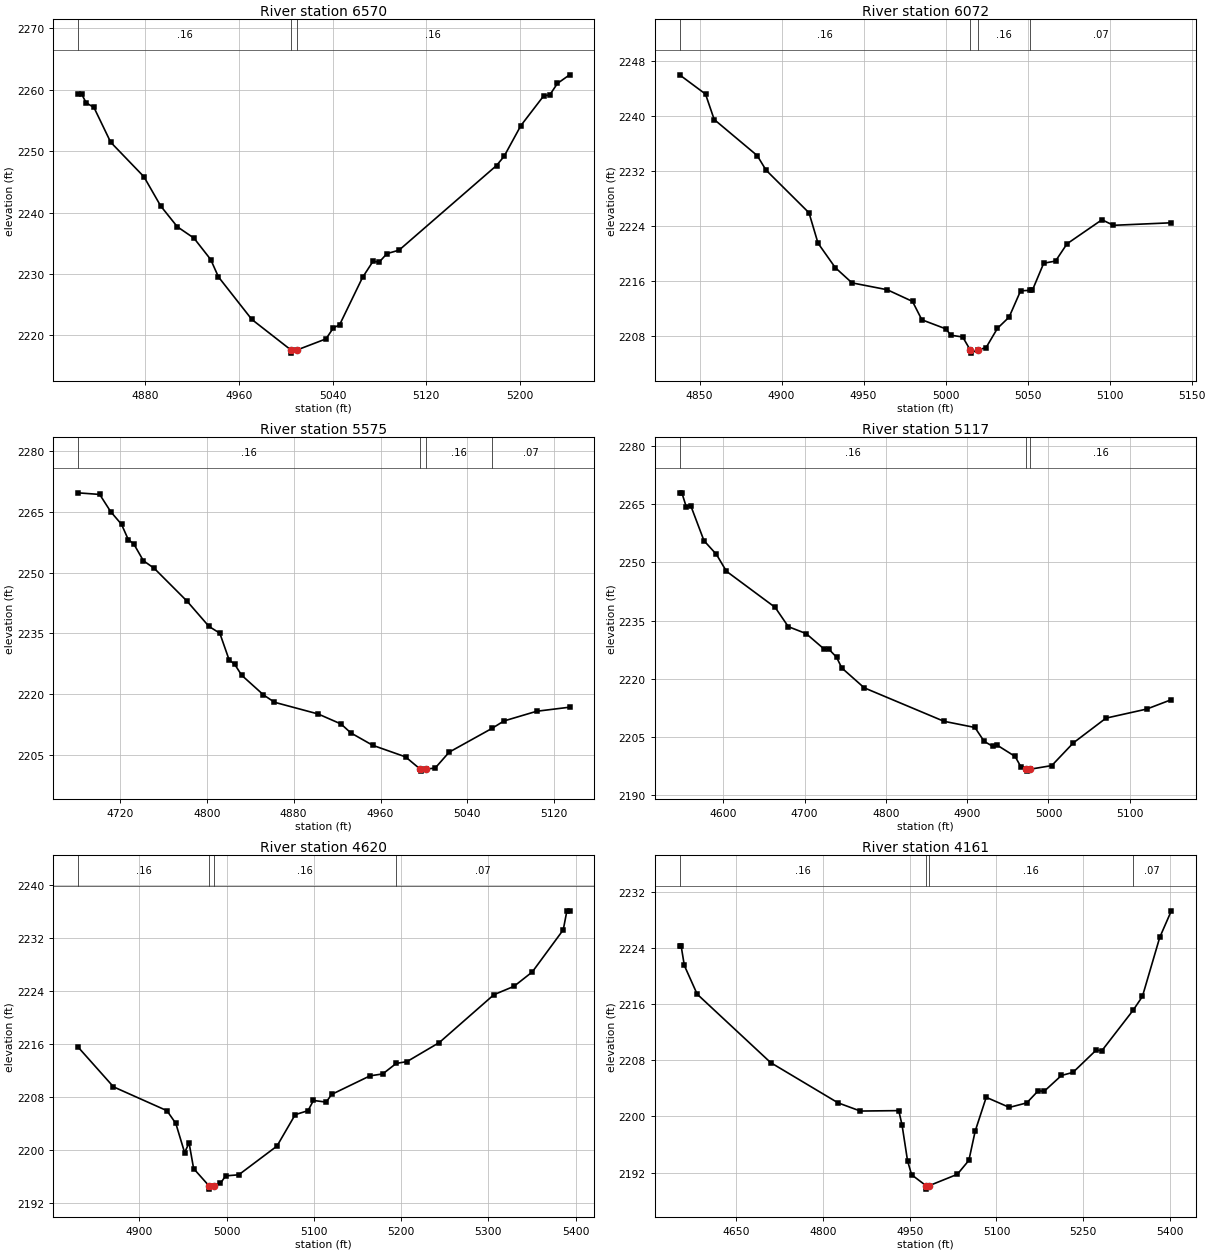
Type RM Length L Ch R = 1,6570,498,498,498
BEGIN DESCRIPTION:
Bitter Creek Trib9 11.0
END DESCRIPTION:
XS GIS Cut Line= 3
      1421404.98      6834438.01      1421271.52      6834555.03
      1421204.99      6834788.02
#Sta/Elev= 30
  4822.5 2259.28  4825.8 2259.28  4829.6 2257.88  4836.2 2257.14  4850.5 2251.47
  4878.9 2245.84  4893.2 2241.08  4907.4 2237.69  4921.6 2235.84  4935.9 2232.35
  4942.5 2229.52  4971.0 2222.59  5004.5 2217.60  5004.8 2217.10  5009.4 2217.60
  5034.3 2219.42  5040.7 2221.23  5045.9 2221.70  5065.5 2229.43  5074.5 2232.07
  5079.7 2231.92  5086.3 2233.31  5096.7 2233.88  5179.9 2247.67  5186.4 2249.18
  5200.7 2254.18  5220.2 2259.03  5225.4 2259.18  5231.9 2261.05  5242.3 2262.45
#Mann=3,-1,0
  4822.5    0.16       0  5004.5    0.07       0  5009.4    0.16       0
Bank Sta=5004.5,5009.4
Exp/Cntr=0.3,0.1

Type RM Length L Ch R = 1,6072,497,497,497
BEGIN DESCRIPTION:
Bitter Creek Trib9 10.0
END DESCRIPTION:
XS GIS Cut Line= 3
      1421155.00      6834138.00      1421001.21      6834189.57
      1420905.03      6834287.97
#Sta/Elev= 30
  4837.8 2246.02  4853.6 2243.22  4858.9 2239.52  4885.1 2234.28  4890.5 2232.16
  4916.7 2225.95  4922.2 2221.53  4932.7 2217.98  4942.9 2215.76  4964.4 2214.76
  4979.8 2213.06  4985.5 2210.39  5000.0 2209.08  5003.3 2208.14  5010.4 2207.89
  5014.9 2206.04  5015.3 2205.54  5019.9 2206.04  5024.6 2206.32  5031.6 2209.15
  5038.7 2210.78  5045.7 2214.60  5051.2 2214.67  5052.9 2214.69  5059.8 2218.62
  5067.0 2218.93  5074.0 2221.44  5095.3 2224.94  5102.3 2224.13  5137.6 2224.50
#Mann=4,-1,0
  4837.8    0.16       0  5014.9    0.07       0  5019.9    0.16       0
  5051.2    0.07       0
Bank Sta=5014.9,5019.9
Exp/Cntr=0.3,0.1

Type RM Length L Ch R = 1,5575,458,458,458
BEGIN DESCRIPTION:
Bitter Creek Trib9 9.0
END DESCRIPTION:
XS GIS Cut Line= 3
      1421104.98      6833738.00      1420788.04      6833771.45
      1420654.97      6833788.00
#Sta/Elev= 30
  4681.3 2269.67  4701.4 2269.27  4711.5 2265.03  4721.5 2261.89  4727.7 2258.14
  4732.8 2257.05  4741.6 2252.93  4751.7 2251.02  4781.8 2242.95  4802.0 2236.72
  4812.0 2235.04  4820.6 2228.44  4825.6 2227.41  4832.1 2224.68  4852.2 2219.83
  4862.3 2218.01  4902.5 2215.12  4923.6 2212.65  4932.7 2210.44  4952.8 2207.39
  4983.0 2204.54  4996.5 2201.52  4996.9 2201.02  5001.5 2201.52  5010.3 2201.77
  5023.2 2205.70  5062.6 2211.56  5073.6 2213.39  5103.8 2215.79  5134.1 2216.79
#Mann=4,-1,0
  4681.3    0.16       0  4996.5    0.07       0  5001.5    0.16       0
  5062.6    0.07       0
Bank Sta=4996.5,5001.5
Exp/Cntr=0.3,0.1

Type RM Length L Ch R = 1,5117,497,497,497
BEGIN DESCRIPTION:
Bitter Creek Trib9 8.0
END DESCRIPTION:
XS GIS Cut Line= 3
      1421105.01      6833588.00      1420705.40      6833372.73
      1420554.98      6833388.00
#Sta/Elev= 30
  4546.1 2267.85  4548.9 2267.85  4554.2 2264.31  4559.9 2264.51  4576.1 2255.54
  4591.5 2251.99  4603.7 2247.68  4663.7 2238.38  4679.9 2233.42  4701.8 2231.64
  4723.7 2227.70  4729.4 2227.71  4739.2 2225.57  4745.7 2222.80  4773.3 2217.69
  4871.4 2209.08  4909.5 2207.49  4920.9 2203.92  4931.4 2202.64  4937.1 2202.91
  4959.0 2200.03  4966.4 2197.24  4972.7 2196.76  4973.1 2196.26  4977.7 2196.76
  5004.1 2197.69  5030.6 2203.52  5070.8 2209.89  5121.0 2212.23  5151.2 2214.64
#Mann=3,-1,0
  4546.1    0.16       0  4972.7    0.07       0  4977.7    0.16       0
Bank Sta=4972.7,4977.7
Exp/Cntr=0.3,0.1

Type RM Length L Ch R = 1,4620,459,459,459
BEGIN DESCRIPTION:
Bitter Creek Trib9 7.0
END DESCRIPTION:
XS GIS Cut Line= 3
      1420705.03      6832937.99      1420538.04      6832971.45
      1420304.99      6833288.02
#Sta/Elev= 30
  4829.7 2215.59  4870.5 2209.56  4931.7 2205.97  4941.9 2204.05  4952.0 2199.64
  4957.1 2201.12  4962.3 2197.24  4979.9 2194.64  4980.3 2194.14  4985.6 2194.64
  4992.9 2194.99  4999.0 2196.14  5014.0 2196.30  5057.8 2200.63  5078.7 2205.37
  5093.4 2205.97  5099.6 2207.51  5114.2 2207.26  5120.4 2208.42  5164.4 2211.22
  5179.0 2211.51  5194.4 2213.09  5206.8 2213.37  5243.8 2216.24  5306.3 2223.45
  5329.4 2224.72  5350.3 2226.88  5385.8 2233.23  5390.0 2236.10  5393.1 2236.10
#Mann=4,-1,0
  4829.7    0.16       0  4979.9    0.07       0  4985.6    0.16       0
  5194.4    0.07       0
Bank Sta=4979.9,4985.6
Exp/Cntr=0.3,0.1

Type RM Length L Ch R = 1,4161,496,496,496
BEGIN DESCRIPTION:
Bitter Creek Trib9 6.0
END DESCRIPTION:
XS GIS Cut Line= 3
      1420704.96      6832388.02      1420307.28      6832593.86
      1419905.02      6832588.00
#Sta/Elev= 30
  4552.2 2224.23  4555.0 2224.23  4560.4 2221.51  4582.6 2217.42  4709.7 2207.66
  4826.1 2201.93  4864.7 2200.76  4931.1 2200.82  4936.8 2198.76  4946.3 2193.66
  4953.3 2191.68  4978.1 2190.13  4978.6 2189.63  4983.9 2190.13  5032.3 2191.74
  5052.3 2193.73  5063.2 2197.89  5082.3 2202.72  5122.3 2201.28  5152.3 2201.92
  5172.3 2203.66  5182.3 2203.56  5212.3 2205.83  5232.3 2206.27  5272.3 2209.44
  5282.3 2209.37  5336.2 2215.12  5352.3 2217.09  5382.3 2225.52  5402.3 2229.30
#Mann=4,-1,0
  4552.2    0.16       0  4978.1    0.07       0  4983.9    0.16       0
  5336.2    0.07       0
Bank Sta=4978.1,4983.9
Exp/Cntr=0.3,0.1

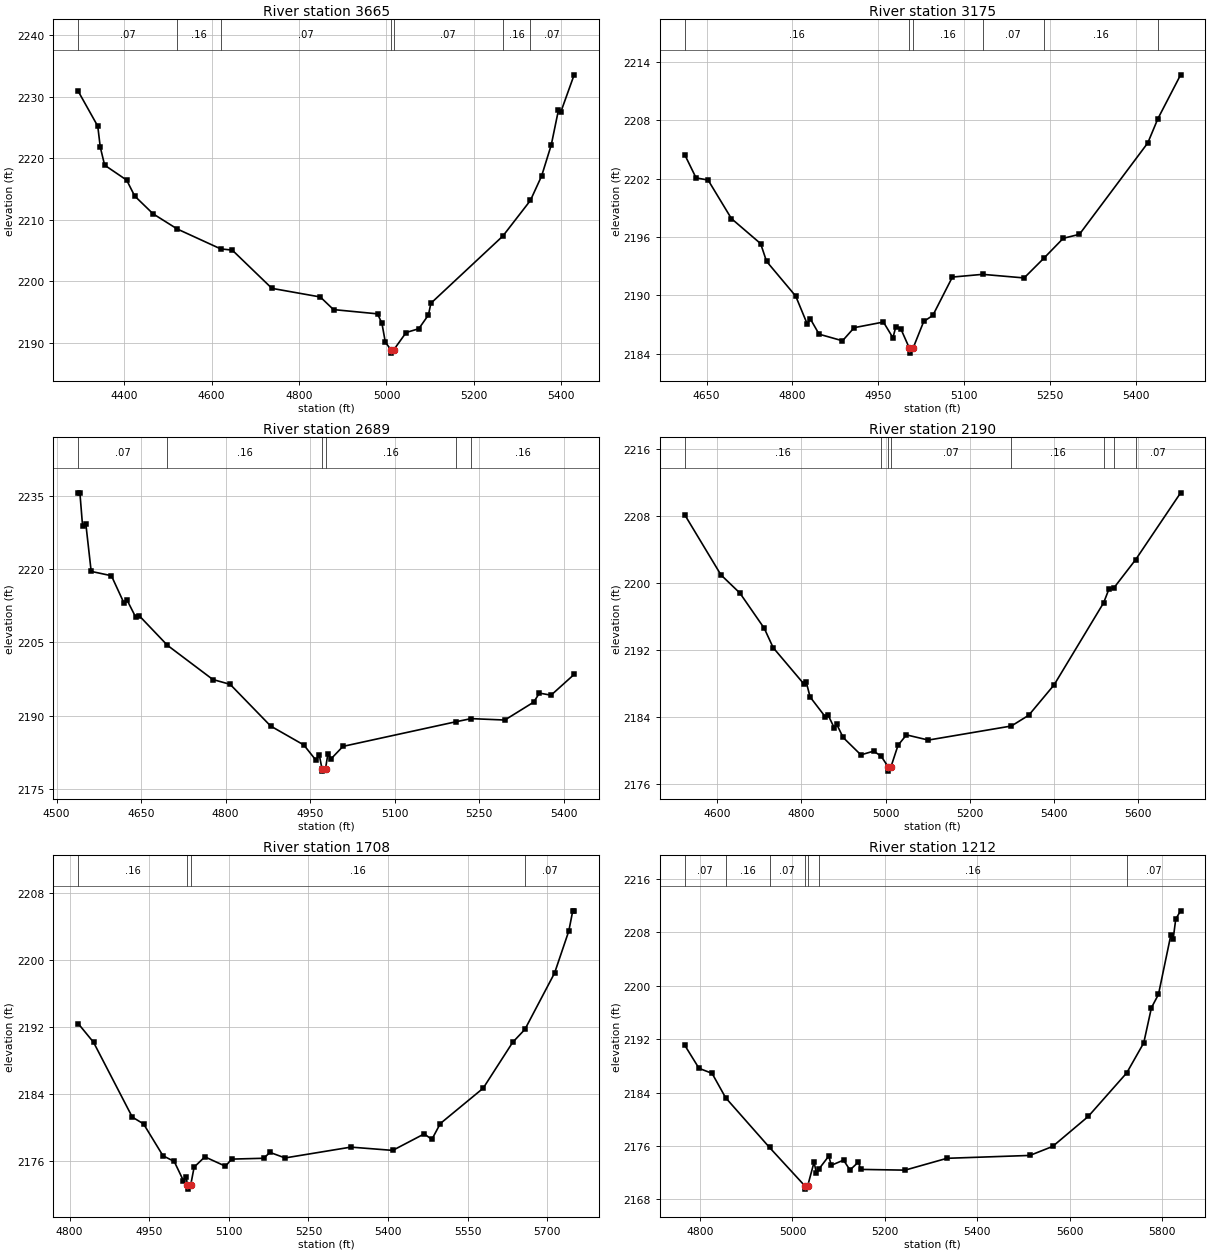
Type RM Length L Ch R = 1,3665,490,490,490
BEGIN DESCRIPTION:
Bitter Creek Trib9 5.0
END DESCRIPTION:
XS GIS Cut Line= 3
      1420755.04      6832288.00      1420054.68      6832208.13
      1419854.98      6832588.04
#Sta/Elev= 30
  4295.1 2230.89  4339.8 2225.22  4345.5 2221.84  4355.5 2218.89  4405.9 2216.46
  4424.2 2213.88  4466.2 2210.99  4521.6 2208.52  4620.9 2205.29  4647.4 2205.09
  4738.0 2198.88  4848.7 2197.48  4878.9 2195.43  4979.5 2194.74  4989.6 2193.22
  4997.3 2190.17  5010.5 2188.86  5011.0 2188.36  5016.3 2188.86  5045.0 2191.71
  5073.9 2192.32  5096.0 2194.56  5101.6 2196.46  5266.1 2207.37  5329.1 2213.15
  5354.8 2217.13  5376.9 2222.19  5393.3 2227.84  5398.9 2227.56  5429.2 2233.56
#Mann=7,-1,0
  4295.1    0.07       0  4521.6    0.16       0  4620.9    0.07       0
  5010.5    0.07       0  5016.3    0.07       0  5266.1    0.16       0
  5329.1    0.07       0
Bank Sta=5010.5,5016.3
Exp/Cntr=0.3,0.1

Type RM Length L Ch R = 1,3175,486,486,486
BEGIN DESCRIPTION:
Bitter Creek Trib9 4.0
END DESCRIPTION:
XS GIS Cut Line= 3
      1419655.00      6831487.99      1419734.69      6831868.13
      1419505.00      6832288.01
#Sta/Elev= 30
  4611.6 2204.48  4631.5 2202.08  4652.5 2201.86  4693.3 2197.89  4744.4 2195.31
  4754.7 2193.49  4805.7 2189.91  4826.0 2187.02  4831.1 2187.58  4846.6 2185.99
  4887.5 2185.31  4907.9 2186.66  4959.0 2187.24  4975.7 2185.62  4980.8 2186.78
  4989.7 2186.51  5004.5 2184.54  5005.0 2184.04  5010.8 2184.54  5029.5 2187.30
  5045.4 2187.92  5079.6 2191.87  5132.5 2192.15  5205.0 2191.78  5239.7 2193.82
  5273.4 2195.86  5301.7 2196.27  5421.2 2205.68  5438.9 2208.18  5478.6 2212.69
#Mann=6,-1,0
  4611.6    0.16       0  5004.5    0.07       0  5010.8    0.16       0
  5132.5    0.07       0  5239.7    0.16       0  5438.9    0.07       0
Bank Sta=5004.5,5010.8
Exp/Cntr=0.3,0.1

Type RM Length L Ch R = 1,2689,499,499,499
BEGIN DESCRIPTION:
Bitter Creek Trib9 3.0
END DESCRIPTION:
XS GIS Cut Line= 3
      1419605.01      6831337.99      1419361.06      6831729.86
      1419455.00      6832137.99
#Sta/Elev= 30
  4538.4 2235.73  4541.4 2235.73  4546.1 2228.97  4552.0 2229.28  4561.4 2219.60
  4597.3 2218.71  4619.3 2213.19  4625.2 2213.68  4640.5 2210.19  4646.4 2210.53
  4696.8 2204.42  4777.4 2197.40  4808.1 2196.41  4880.0 2187.85  4938.9 2183.96
  4960.4 2180.83  4966.3 2181.96  4971.1 2179.09  4971.6 2178.59  4977.4 2179.09
  4981.6 2182.09  4987.5 2181.14  5008.4 2183.67  5208.6 2188.72  5235.9 2189.37
  5295.7 2189.08  5346.9 2192.75  5357.2 2194.61  5377.8 2194.18  5418.8 2198.45
#Mann=6,-1,0
  4538.4    0.07       0  4696.8    0.16       0  4971.1    0.07       0
  4977.4    0.16       0  5208.6    0.07       0  5235.9    0.16       0
Bank Sta=4971.1,4977.4
Exp/Cntr=0.3,0.1

Type RM Length L Ch R = 1,2190,482,482,482
BEGIN DESCRIPTION:
Bitter Creek Trib9 2.0
END DESCRIPTION:
XS GIS Cut Line= 3
      1419155.03      6831337.96      1418895.72      6831738.45
      1418855.00      6832437.96
#Sta/Elev= 30
  4522.9 2208.21  4609.0 2201.02  4654.0 2198.85  4711.9 2194.64  4733.0 2192.33
  4805.5 2188.02  4811.5 2188.24  4820.7 2186.44  4856.5 2184.09  4862.9 2184.34
  4878.1 2182.75  4884.0 2183.17  4899.2 2181.60  4941.4 2179.52  4971.7 2179.97
  4989.3 2179.37  5006.4 2178.08  5006.9 2177.58  5012.7 2178.08  5029.6 2180.67
  5049.6 2181.91  5101.6 2181.29  5298.8 2182.97  5340.1 2184.26  5400.2 2187.88
  5517.9 2197.69  5530.5 2199.33  5542.3 2199.47  5593.9 2202.84  5700.7 2210.82
#Mann=8,-1,0
  4522.9    0.16       0  4989.3    0.07       0  5006.4    0.07       0
  5012.7    0.07       0  5298.8    0.16       0  5517.9    0.07       0
  5542.3    0.16       0  5593.9    0.07       0
Bank Sta=5006.4,5012.7
Exp/Cntr=0.3,0.1

Type RM Length L Ch R = 1,1708,496,496,496
BEGIN DESCRIPTION:
Bitter Creek Trib9 1.0
END DESCRIPTION:
XS GIS Cut Line= 3
      1418355.00      6831488.00      1418452.65      6831643.71
      1418355.00      6832388.03
#Sta/Elev= 30
  4816.2 2192.41  4845.1 2190.18  4918.1 2181.26  4939.3 2180.45  4975.9 2176.65
  4997.1 2175.97  5014.4 2173.68  5019.9 2174.08  5021.8 2173.17  5022.3 2172.67
  5028.2 2173.17  5034.6 2175.29  5054.8 2176.52  5093.7 2175.40  5105.2 2176.25
  5165.7 2176.35  5177.5 2177.05  5206.0 2176.39  5330.0 2177.68  5408.8 2177.29
  5468.3 2179.26  5482.5 2178.59  5498.5 2180.49  5579.2 2184.70  5635.0 2190.19
  5657.9 2191.72  5713.8 2198.44  5740.6 2203.45  5748.1 2205.86  5750.7 2205.86
#Mann=4,-1,0
  4816.2    0.16       0  5021.8    0.07       0  5028.2    0.16       0
  5657.9    0.07       0
Bank Sta=5021.8,5028.2
Exp/Cntr=0.3,0.1

Type RM Length L Ch R = 1,1212,370,370,370
BEGIN DESCRIPTION:
Bitter Creek Trib10 43.0
END DESCRIPTION:
XS GIS Cut Line= 3
      1418254.96      6831488.02      1418045.20      6831589.70
      1418305.00      6832387.99
#Sta/Elev= 30
  4766.9 2191.09  4797.9 2187.62  4826.1 2186.87  4855.5 2183.22  4950.4 2175.78
  5026.6 2170.05  5027.1 2169.55  5033.0 2170.05  5046.7 2173.58  5051.9 2171.92
  5056.5 2172.49  5078.6 2174.50  5083.9 2173.11  5110.5 2173.89  5124.4 2172.41
  5142.5 2173.59  5147.7 2172.50  5243.5 2172.39  5334.1 2174.16  5513.5 2174.59
  5562.8 2175.94  5639.7 2180.42  5723.0 2186.94  5759.7 2191.42  5776.4 2196.69
  5791.6 2198.68  5818.3 2207.55  5823.5 2207.02  5829.0 2209.96  5839.5 2211.18
#Mann=7,-1,0
  4766.9    0.07       0  4855.5    0.16       0  4950.4    0.07       0
  5026.6    0.07       0  5033.0    0.07       0  5056.5    0.16       0
  5723.0    0.07       0
Bank Sta=5026.6,5033
Exp/Cntr=0.3,0.1

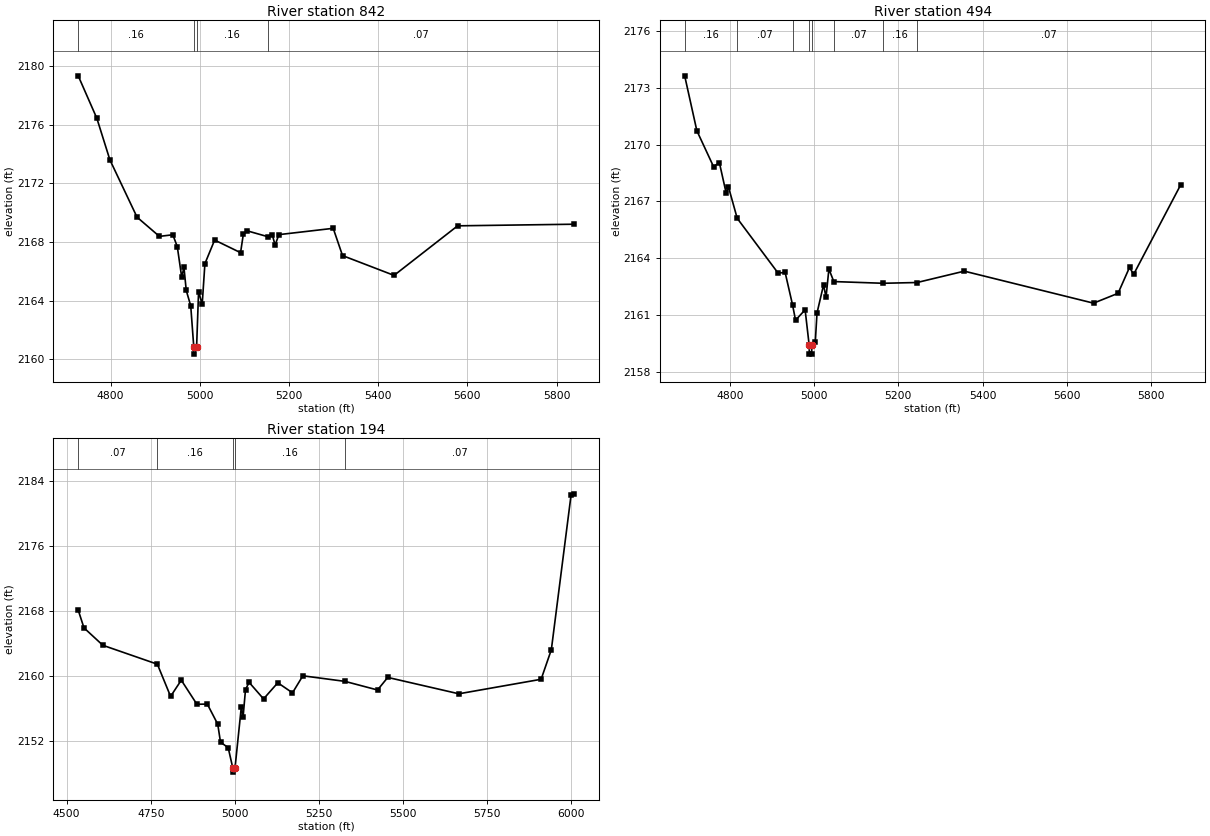
Type RM Length L Ch R = 1,842,348,348,348
BEGIN DESCRIPTION:
Bitter Creek Trib9 4314
END DESCRIPTION:
XS GIS Cut Line= 3
      1418126.69      6831327.65      1417854.81      6831310.80
      1417366.80      6831993.64
#Sta/Elev= 30
  4727.6 2179.33  4769.4 2176.43  4798.6 2173.60  4859.5 2169.69  4909.6 2168.38
  4939.7 2168.49  4949.7 2167.68  4959.6 2165.59  4964.6 2166.27  4969.8 2164.69
  4979.8 2163.65  4986.6 2160.85  4987.1 2160.35  4993.0 2160.85  4997.4 2164.62
  5005.5 2163.74  5011.6 2166.52  5033.4 2168.13  5091.5 2167.27  5097.7 2168.52
  5106.2 2168.76  5152.6 2168.36  5162.8 2168.47  5168.9 2167.79  5177.5 2168.50
  5299.2 2168.93  5320.1 2167.07  5435.6 2165.72  5578.1 2169.10  5839.3 2169.21
#Mann=4,-1,0
  4727.6    0.16       0  4986.6    0.07       0  4993.0    0.16       0
  5152.6    0.07       0
Bank Sta=4986.6,4993
Exp/Cntr=0.3,0.1

Type RM Length L Ch R = 1,494,300,300,300
BEGIN DESCRIPTION:
Bitter Creek Trib9 4313
END DESCRIPTION:
XS GIS Cut Line= 3
      1418091.97      6831088.06      1417805.16      6830978.84
      1417060.75      6831428.35
#Sta/Elev= 30
  4693.1 2173.63  4722.0 2170.73  4761.5 2168.84  4775.5 2169.04  4791.6 2167.43
  4796.9 2167.77  4817.7 2166.11  4914.6 2163.22  4931.4 2163.25  4948.9 2161.55
  4956.1 2160.73  4978.8 2161.28  4988.3 2159.44  4988.8 2158.94  4994.3 2158.94
  4994.8 2159.44  5003.0 2159.60  5007.0 2161.11  5022.6 2162.60  5028.4 2161.93
  5035.2 2163.43  5046.9 2162.77  5163.9 2162.68  5244.4 2162.72  5356.4 2163.32
  5663.0 2161.63  5721.2 2162.15  5748.4 2163.52  5758.1 2163.15  5869.6 2167.87
#Mann=8,-1,0
  4693.1    0.16       0  4817.7    0.07       0  4948.9    0.16       0
  4988.3    0.07       0  4994.8    0.16       0  5046.9    0.07       0
  5163.9    0.16       0  5244.4    0.07       0
Bank Sta=4988.3,4994.8
Exp/Cntr=0.3,0.1

Type RM Length L Ch R = 1,194,0,0,0
BEGIN DESCRIPTION:
Bitter Creek Trib9 4316
END DESCRIPTION:
XS GIS Cut Line= 4
      1418144.14      6830869.34      1417704.79      6830715.21
      1417196.30      6830902.49      1416984.38      6831318.43
#Sta/Elev= 30
  4534.4 2168.13  4551.5 2165.94  4607.7 2163.79  4769.7 2161.46  4809.0 2157.49
  4840.8 2159.49  4887.2 2156.52  4918.2 2156.54  4949.2 2154.06  4957.4 2151.84
  4980.2 2151.17  4994.0 2148.65  4994.5 2148.15  5000.5 2148.65  5019.2 2156.16
  5024.5 2154.93  5031.7 2158.33  5042.4 2159.22  5085.4 2157.18  5127.7 2159.17
  5171.4 2157.93  5202.2 2160.03  5327.6 2159.34  5424.2 2158.28  5454.6 2159.83
  5665.9 2157.81  5910.5 2159.60  5940.9 2163.25  5999.5 2182.32  6008.7 2182.47
#Mann=5,-1,0
  4534.4    0.07       0  4769.7    0.16       0  4994.0    0.07       0
  5000.5    0.16       0  5327.6    0.07       0
Bank Sta=4994,5000.5
Exp/Cntr=0.3,0.1

Chan Stop Cuts=-1