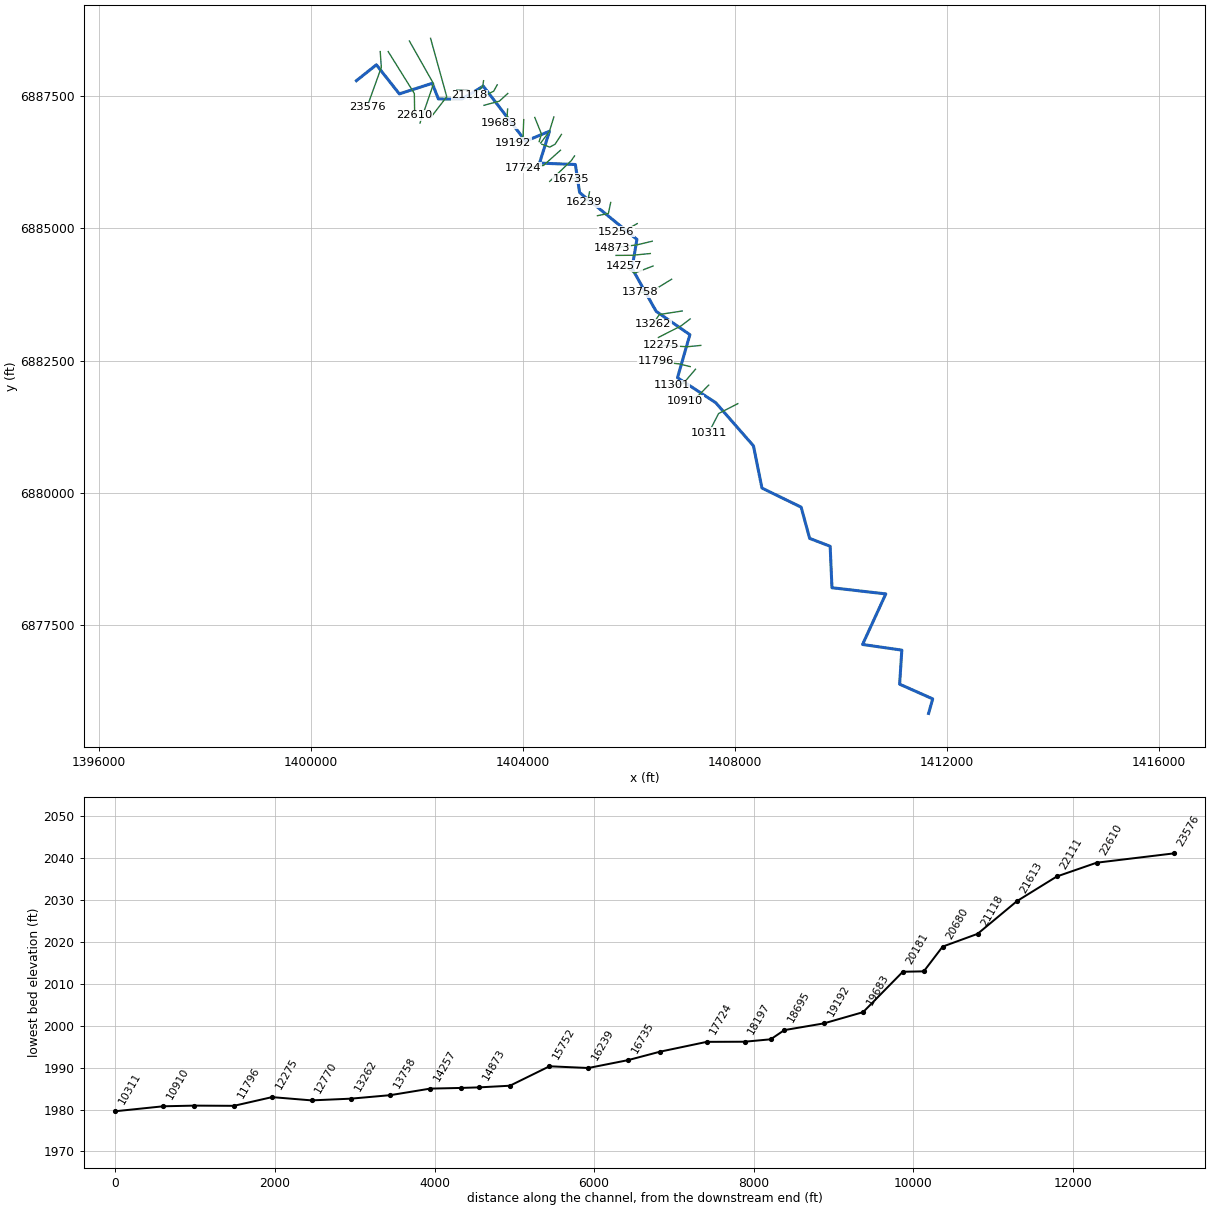
--- Bluff Creek.prj (project) ---

Proj Title=Bluff Creek Base Level Engineering
Current Plan=p01
Default Exp/Contr=0.3,0.1
English Units
Geom File=g01
Flow File=f01
Plan File=p01
Y Axis Title=Elevation
X Axis Title(PF)=Main Channel Distance
X Axis Title(XS)=Station
BEGIN DESCRIPTION:
Bluff Creek
END DESCRIPTION:
DSS Export Rating Curves= 0
DSS Export Rating Curve Sorted= 0
DSS Export Volume Flow Curves= 0
DXF OffsetX= 0
DXF OffsetY= 0
DXF ScaleX= 1
DXF ScaleY= 10

--- Bluff Creek.p01 (plan) ---

Plan Title=Multiple Run
Short Identifier=Multiple
Geom File=g01
Flow File=f01
Subcritical Flow
K Sum by GR= 0
Std Step Tol= 0.01
Critical Tol= 0.01
Num of Std Step Trials= 20
Max Error Tol= 0.3
Flow Tol Ratio= 0.001
Split Flow NTrial= 30
Split Flow Tol= 0.02
Split Flow Ratio= 0.02
Log Output Level= 0
Friction Slope Method= 1
Unsteady Friction Slope Method= 2
Unsteady Bridges Friction Slope Method= 1
Parabolic Critical Depth
Global Vel Dist=  1 , 1 , 1
Global Log Level= 0
CheckData=True
Encroach Param= -1, 0, 0, 0
BEGIN DESCRIPTION:
Multiple Run
END DESCRIPTION:

--- Bluff Creek.f01 (steady flow) ---

Flow Title=Multiple
Number of Profiles=7
Profile Names=10-year,25-year,50-year,1pct_min,100-year,1pct_plu,500-year
River Rch & RM= Bluff Creek,Reach-1,23576
     317     448     559     347     692    1380    1072
River Rch & RM= Bluff Creek,Reach-1,19683
     859    1287    1666    1070    2134    4258    3549
River Rch & RM= Bluff Creek,Reach-1,15752
    1185    1785    2320    1492    2977    5941    4972
River Rch & RM= Bluff Creek,Reach-1,13758
    1271    1920    2499    1610    3212    6409    5380
River Rch & RM= Bluff Creek,Reach-1,10910
    1296    1959    2550    1643    3279    6542    5494
River Rch & RM= Bluff Creek,Reach-1,10311
    1360    2055    2676    1724    3441    6865    5765
River Rch & RM= Bluff Creek,Reach-1,8597
    1318    1982    2572    1651    3294    6572    5477
Boundary for River Rch & Prof#=Bluff Creek,Reach-1,1
Up Type=0
Dn Type=3
Dn Slope=0.005
Boundary for River Rch & Prof#=Bluff Creek,Reach-1,2
Up Type=0
Dn Type=3
Dn Slope=0.005
Boundary for River Rch & Prof#=Bluff Creek,Reach-1,3
Up Type=0
Dn Type=3
Dn Slope=0.005
Boundary for River Rch & Prof#=Bluff Creek,Reach-1,4
Up Type=0
Dn Type=3
Dn Slope=0.005
Boundary for River Rch & Prof#=Bluff Creek,Reach-1,5
Up Type=0
Dn Type=3
Dn Slope=0.005
Boundary for River Rch & Prof#=Bluff Creek,Reach-1,6
Up Type=0
Dn Type=3
Dn Slope=0.005
Boundary for River Rch & Prof#=Bluff Creek,Reach-1,7
Up Type=0
Dn Type=3
Dn Slope=0.005

--- Bluff Creek.g01 (geometry) ---

Geom Title=Existing Conditions
Program Version=4.10

River Reach=Bluff Creek     ,Reach-1
Reach XY= 30
        1400855.        6887788.      1401232.32      6888088.11
      1401665.48      6887538.93      1402286.64      6887738.45
      1402402.29      6887443.28      1402839.93      6887438.18
      1403249.48      6887685.65      1404048.59      6886645.63
      1404499.45      6886833.23      1404312.34      6886231.67
      1404988.36      6886204.75      1405068.47      6885674.43
      1406149.53      6884790.45      1406057.15      6884243.97
      1406512.81      6883431.81      1407149.67      6882990.66
      1406915.76      6882178.32      1407638.72      6881705.14
      1408349.54      6880890.45      1408510.18      6880093.41
      1409249.59      6879732.82      1409410.03      6879143.08
       1409797.2      6878994.21      1409831.27      6878211.11
       1410847.2      6878094.21      1410408.82      6877139.58
      1411149.83      6877032.59      1411108.54      6876389.44
      1411732.46      6876111.83        1411655.        6875838.

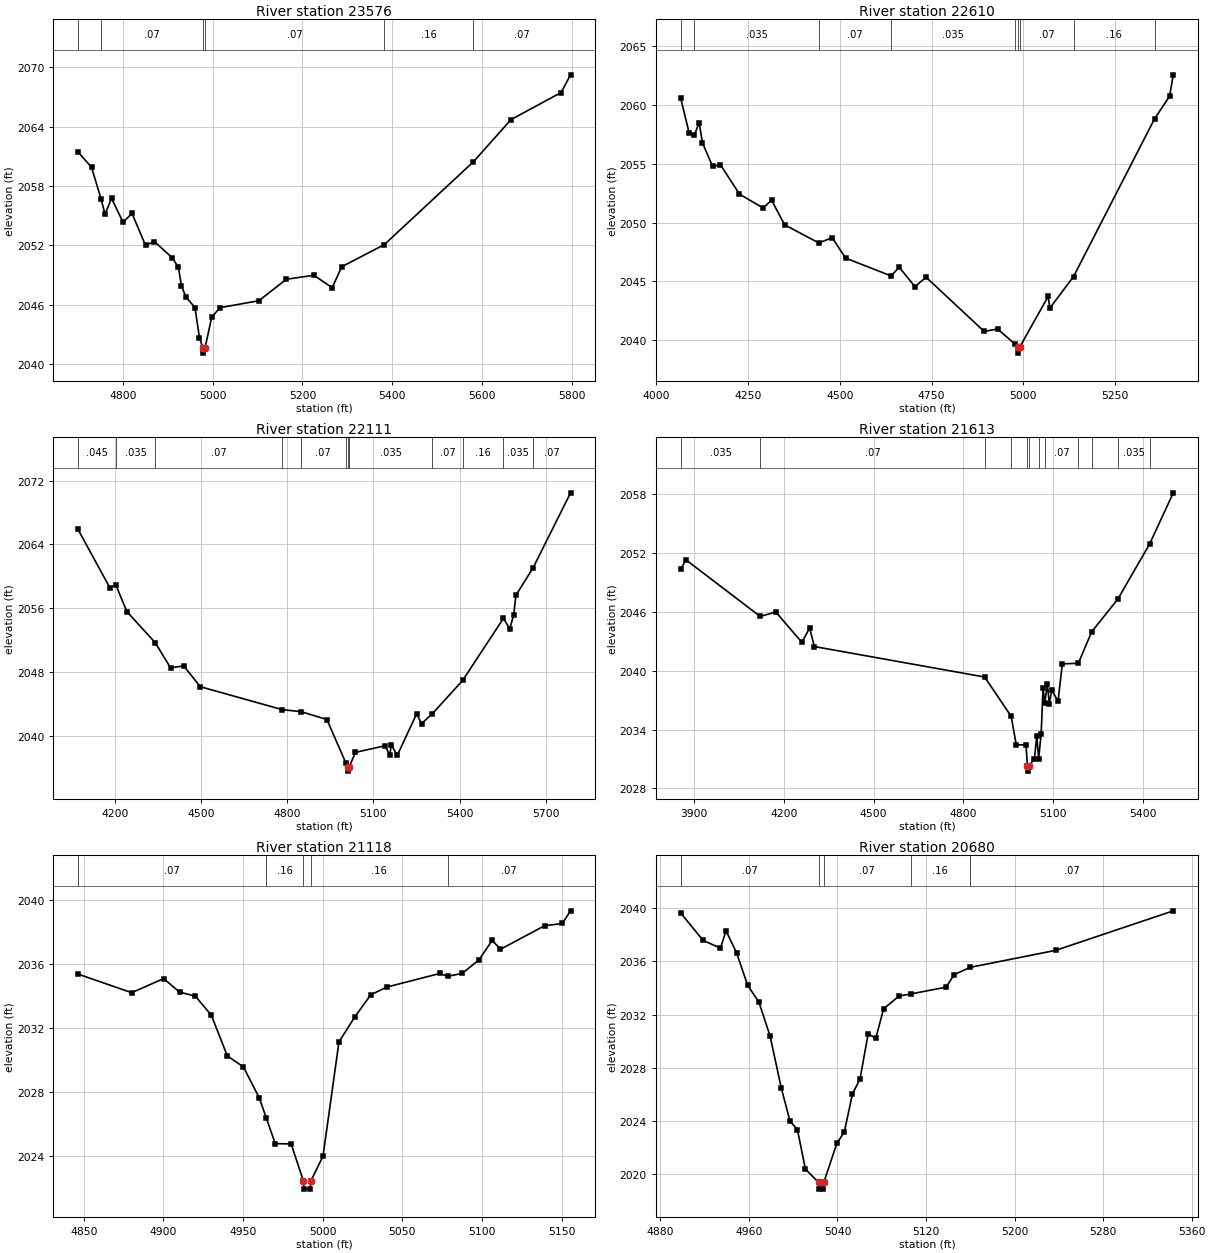
Type RM Length L Ch R = 1 ,23576   ,966,966,966
BEGIN DESCRIPTION:
Bluff Creek 37.0
END DESCRIPTION:
XS GIS Cut Line= 3
        1401305.      6888338.05      1401325.28      6888038.53
      1401055.01      6887288.02
#Sta/Elev= 30
  4699.8 2061.44  4729.9 2059.89  4750.9 2056.73    4760 2055.15  4774.4 2056.76
  4800.1 2054.35  4820.1 2055.23  4850.2 2052.02  4870.2 2052.39  4910.3 2050.74
  4923.6 2049.78  4930.4 2047.88  4940.4  2046.8  4960.4 2045.73  4970.5 2042.68
  4978.3 2041.63  4978.6 2041.13  4982.7 2041.63  4997.8 2044.75    5016 2045.72
  5102.8 2046.42  5164.2 2048.59  5225.6 2048.99  5266.3 2047.73  5287.5 2049.85
  5382.6 2052.09  5581.1 2060.45  5664.9 2064.71  5776.5 2067.44  5797.7 2069.23
#Mann= 6 ,-1 , 0
  4699.8    .035       0  4750.9     .07       0  4978.3     .07       0
  4982.7     .07       0  5382.6     .16       0  5581.1     .07       0
Bank Sta=4978.3,4982.7
XS Rating Curve= 0 ,0
Exp/Cntr=0.3,0.1

Type RM Length L Ch R = 1 ,22610   ,499,499,499
BEGIN DESCRIPTION:
Bluff Creek 36.0
END DESCRIPTION:
XS GIS Cut Line= 3
      1401454.99      6888338.02      1401948.94      6887546.15
        1401955.      6887137.99
#Sta/Elev= 30
  4066.7 2060.53  4089.7 2057.59  4103.3 2057.39  4116.9 2058.49  4125.6 2056.79
  4153.4 2054.76  4174.7 2054.91  4226.6 2052.41  4290.7 2051.24  4314.2 2051.89
  4349.6  2049.8  4442.6 2048.27  4479.2 2048.71  4515.6 2046.98  4639.2 2045.47
  4661.9  2046.2  4704.4 2044.56  4735.1 2045.35  4893.1 2040.75  4929.7 2040.96
  4977.8 2039.65  4985.3 2039.41  4985.6 2038.91  4989.8 2039.41  5067.2 2043.72
  5072.2 2042.74  5136.5 2045.41  5357.1  2058.8  5398.2 2060.73  5408.2 2062.54
#Mann= 9 ,-1 , 0
  4066.7     .07       0  4103.3    .035       0  4442.6     .07       0
  4639.2    .035       0  4977.8     .07       0  4985.3     .07       0
  4989.8     .07       0  5136.5     .16       0  5357.1    .035       0
Bank Sta=4985.3,4989.8
XS Rating Curve= 0 ,0
Exp/Cntr=0.3,0.1

Type RM Length L Ch R = 1 ,22111   ,498,498,498
BEGIN DESCRIPTION:
Bluff Creek 35.0
END DESCRIPTION:
XS GIS Cut Line= 3
      1401854.99      6888538.02      1402311.36      6887730.68
        1402055.      6886987.99
#Sta/Elev= 30
  4072.6 2065.87  4183.1 2058.59  4204.4  2058.9  4242.3  2055.6  4341.5 2051.68
  4394.3 2048.55  4440.2 2048.79  4497.7 2046.19  4782.5 2043.32  4847.8 2043.07
  4938.1 2042.08  5003.4  2036.7  5011.2 2036.12  5011.5 2035.62  5015.7 2036.12
  5037.3 2037.97  5140.4 2038.79  5156.8 2037.62  5162.1 2038.94  5182.7 2037.58
  5250.4  2042.8  5267.3 2041.57  5304.8  2042.8  5410.2 2046.97  5552.3 2054.75
  5574.1 2053.43  5588.2 2055.22  5595.3 2057.62  5655.2 2061.06  5785.7 2070.46
#Mann= 12 ,-1 , 0
  4072.6    .045       0  4204.4    .035       0  4341.5     .07       0
  4782.5    .035       0  4847.8     .07       0  5003.4    .035       0
  5011.2     .07       0  5015.7    .035       0  5304.8     .07       0
  5410.2     .16       0  5552.3    .035       0  5655.2     .07       0
Bank Sta=5011.2,5015.7
XS Rating Curve= 0 ,0
Exp/Cntr=0.3,0.1

Type RM Length L Ch R = 1 ,21613   ,495,495,495
BEGIN DESCRIPTION:
Bluff Creek 34.0
END DESCRIPTION:
XS GIS Cut Line= 3
      1402255.01      6888587.97      1402560.53      6887485.63
      1402254.97      6887087.97
#Sta/Elev= 30
  3856.1 2050.35  3873.2 2051.32  4121.5 2045.54  4173.4    2046  4260.8  2042.9
  4286.7 2044.37  4302.3 2042.47  4871.3 2039.36  4959.9 2035.35  4976.8 2032.47
  5009.6 2032.41  5014.3 2030.26  5014.7 2029.76  5018.9 2030.26  5037.4 2030.99
  5045.6 2033.36  5051.7 2031.01  5060.1 2033.57  5066.4 2038.25  5072.1 2036.69
    5081 2038.69  5087.3  2036.6  5095.5 2038.05  5116.3 2036.87  5130.8  2040.7
  5184.3 2040.76  5228.8 2043.97  5316.3 2047.31  5422.6 2052.94  5501.5 2058.15
#Mann= 12 ,-1 , 0
  3856.1    .035       0  4121.5     .07       0  4871.3    .035       0
  4959.9     .07       0  5014.3     .07       0  5018.9     .07       0
  5051.7    .035       0  5072.1     .07       0  5184.3    .035       0
  5228.8     .16       0  5316.3    .035       0  5422.6     .07       0
Bank Sta=5014.3,5018.9
XS Rating Curve= 0 ,0
Exp/Cntr=0.3,0.1

Type RM Length L Ch R = 1 ,21118   ,438,438,438
BEGIN DESCRIPTION:
Bluff Creek 33.0
END DESCRIPTION:
XS GIS Cut Line= 3
       1402751.3      6887610.22      1402966.01      6887603.34
      1402993.44      6887513.03
#Sta/Elev= 30
  4846.4 2035.35  4880.1 2034.19  4900.1 2035.07  4910.1 2034.23  4920.1 2033.97
  4930.1 2032.78  4940.1 2030.25  4950.2 2029.56  4960.2 2027.62  4964.5 2026.39
  4970.2 2024.77  4980.2 2024.75  4987.9 2022.43  4988.2 2021.93  4992.2 2021.93
  4992.5 2022.43  5000.2 2023.99  5010.2 2031.12  5020.2 2032.69  5030.2 2034.06
  5040.2 2034.54  5073.5 2035.39  5078.4 2035.21  5087.7  2035.4  5098.2 2036.25
  5106.4 2037.46  5111.6  2036.9  5139.3 2038.37  5150.4 2038.51  5155.6  2039.3
#Mann= 5 ,-1 , 0
  4846.4     .07       0  4964.5     .16       0  4987.9     .07       0
  4992.5     .16       0  5078.4     .07       0
Bank Sta=4987.9,4992.5
XS Rating Curve= 0 ,0
Exp/Cntr=0.3,0.1

Type RM Length L Ch R = 1 ,20680   ,236,236,236
BEGIN DESCRIPTION:
Bluff Creek 32.0
END DESCRIPTION:
XS GIS Cut Line= 3
        1403255.      6887787.97      1403241.09      6887687.33
      1403004.98      6887437.98
#Sta/Elev= 30
  4898.4 2039.63  4918.6 2037.58  4934.3 2036.99  4939.3  2038.3  4948.8 2036.65
  4958.9 2034.19    4969 2032.94  4979.1 2030.39  4989.2 2026.49  4997.1 2023.99
  5003.8 2023.36    5011 2020.39  5022.9 2019.38  5023.2 2018.88  5027.2 2018.88
  5027.6 2019.38  5039.4 2022.31  5046.2 2023.19  5053.5 2026.03  5060.4 2027.17
  5067.7 2030.55  5074.6 2030.22  5081.7 2032.44  5095.6 2033.39  5106.1 2033.55
  5138.1 2034.06  5145.4    2035  5159.8 2035.55  5237.2 2036.83  5343.4  2039.8
#Mann= 5 ,-1 , 0
  4898.4     .07       0  5022.9     .07       0  5027.6     .07       0
  5106.1     .16       0  5159.8     .07       0
Bank Sta=5022.9,5027.6
XS Rating Curve= 0 ,0
Exp/Cntr=0.3,0.1

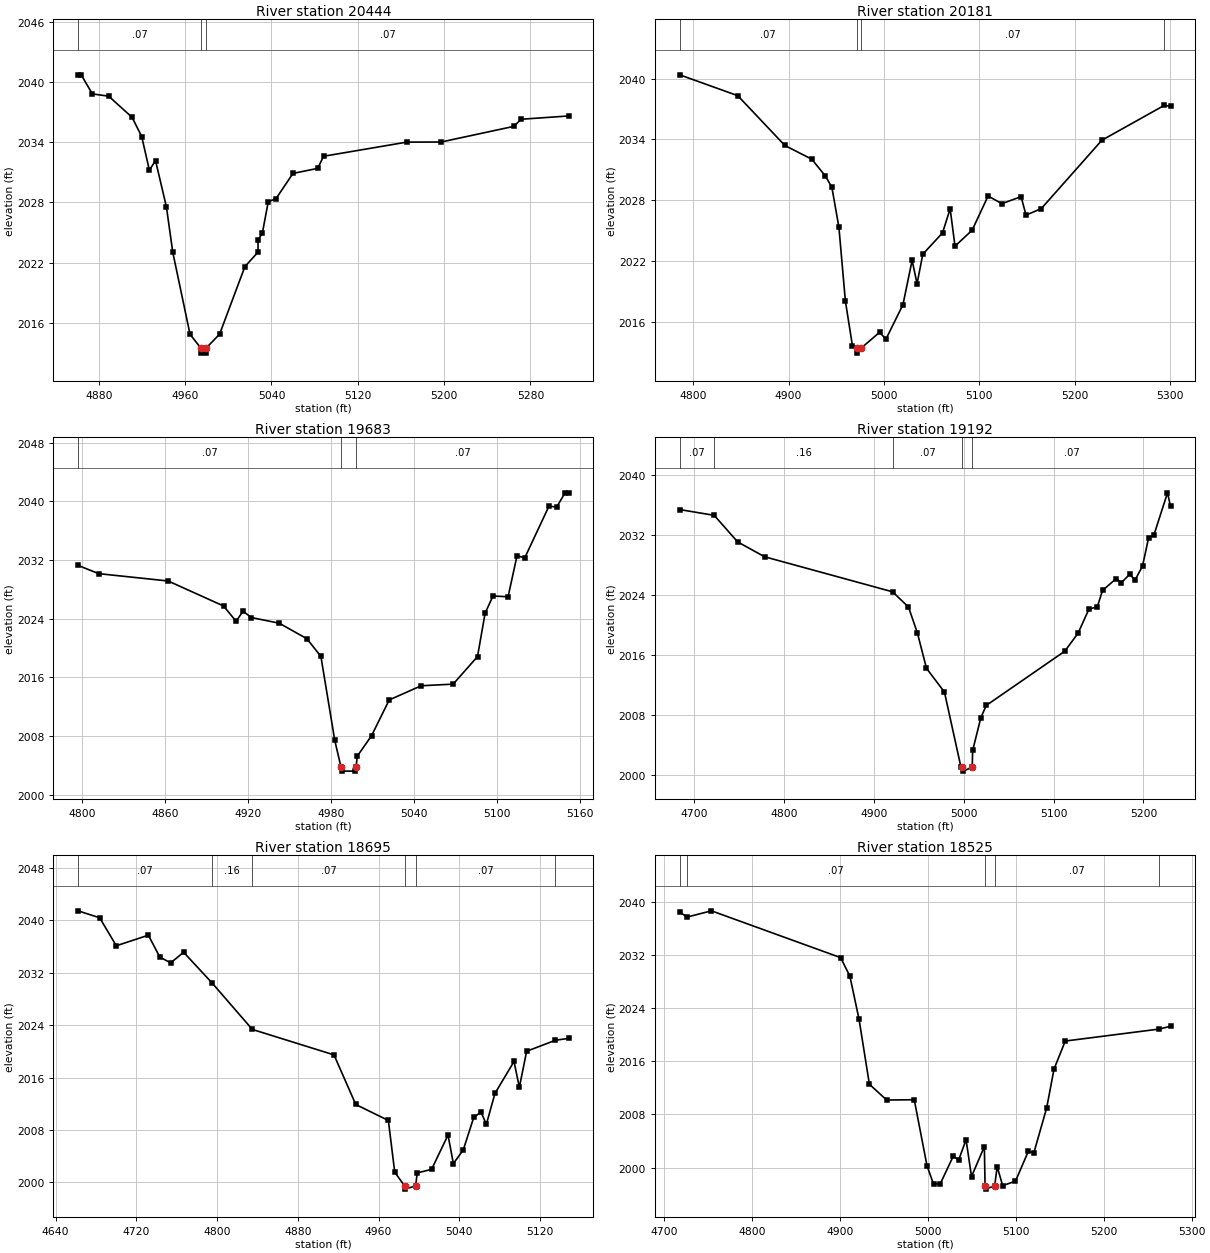
Type RM Length L Ch R = 1 ,20444   ,263,263,263
BEGIN DESCRIPTION:
Bluff Creek 4447
END DESCRIPTION:
XS GIS Cut Line= 3
      1403512.97      6887709.59      1403444.97       6887587.9
      1403158.73      6887454.97
#Sta/Elev= 30
  4860.6 2040.73  4863.6 2040.73  4873.9 2038.83  4889.1  2038.6  4910.8 2036.49
  4919.7 2034.57  4926.8 2031.22  4932.5 2032.18  4942.6 2027.56  4948.5 2023.03
  4964.5 2014.85  4974.6 2013.48  4974.9 2012.98    4979 2012.98  4979.4 2013.48
  4991.9 2014.87 5015.35 2021.61 5027.52 2023.05 5027.52 2024.27  5031.5 2024.93
    5037 2028.08  5044.1 2028.37  5059.9  2030.9  5082.8  2031.4  5088.3 2032.61
  5165.4 2034.02  5197.2 2034.03  5264.6 2035.59  5271.4  2036.3  5315.6 2036.63
#Mann= 3 ,-1 , 0
  4860.6     .07       0  4974.6     .07       0  4979.4     .07       0
Bank Sta=4974.6,4979.4
XS Rating Curve= 0 ,0
Exp/Cntr=0.3,0.1

Type RM Length L Ch R = 1 ,20181   ,498,498,498
BEGIN DESCRIPTION:
Bluff Creek 31.0
END DESCRIPTION:
XS GIS Cut Line= 3
      1403712.41      6887546.47      1403554.33      6887401.93
      1403264.13      6887323.15
#Sta/Elev= 30
  4785.8 2040.38  4846.7 2038.32  4896.1  2033.4  4924.4 2032.04  4938.6 2030.38
  4945.4 2029.28  4952.8 2025.33  4959.6 2018.03    4967 2013.61  4971.4 2013.38
  4971.7 2012.88  4976.2 2013.38  4995.4 2014.93  5002.2 2014.27    5020 2017.67
  5029.6 2022.05  5034.8 2019.74  5040.8 2022.65  5061.5 2024.76  5069.5 2027.14
  5074.6 2023.45  5092.6 2025.03  5109.3 2028.41  5123.7 2027.65  5143.9 2028.34
  5149.1 2026.52  5165.1 2027.16  5228.7 2033.92  5294.1 2037.36  5300.7 2037.27
#Mann= 4 ,-1 , 0
  4785.8     .07       0  4971.4     .07       0  4976.2     .07       0
  5294.1     .16       0
Bank Sta=4971.4,4976.2
XS Rating Curve= 0 ,0
Exp/Cntr=0.3,0.1

Type RM Length L Ch R = 1 ,19683   ,491,491,491
BEGIN DESCRIPTION:
Bluff Creek 30.0
END DESCRIPTION:
XS GIS Cut Line= 3
      1403709.51        6887253.      1403693.18      6887050.46
      1403555.03      6886988.01
#Sta/Elev= 30
  4796.8 2031.27  4811.8 2030.14    4862 2029.14  4902.1 2025.73  4911.1 2023.65
  4916.1 2025.02  4922.2 2024.16  4942.3 2023.39  4962.3 2021.27  4972.4 2018.87
  4982.4 2007.45    4987 2003.74  4987.5 2003.24  4997.3 2003.24  4997.8 2003.74
  4998.7 2005.28    5009 2008.06  5021.8 2012.94  5044.9 2014.87    5068 2015.09
  5085.6 2018.84  5091.1 2024.76  5096.8  2027.1  5107.7 2026.99  5114.2 2032.61
  5119.7 2032.27  5137.3 2039.35  5142.8  2039.2  5148.9 2041.15  5151.6 2041.15
#Mann= 3 ,-1 , 0
  4796.8     .07       0    4987     .07       0  4997.8     .07       0
Bank Sta=4987,4997.8
XS Rating Curve= 0 ,0
Exp/Cntr=0.3,0.1

Type RM Length L Ch R = 1 ,19192   ,497,497,497
BEGIN DESCRIPTION:
Bluff Creek 29.0
END DESCRIPTION:
XS GIS Cut Line= 4
      1404013.22      6887052.43        1404005.        6886838.
      1404001.11      6886736.56      1403808.98      6886609.95
#Sta/Elev= 30
  4683.9 2035.41  4722.3 2034.64  4748.4  2031.1  4778.4 2029.12  4920.8 2024.45
  4938.5 2022.42  4948.5 2018.93  4958.5 2014.26  4978.5 2011.09  4996.8 2001.14
  4998.5 2001.06    4999 2000.56  5009.4 2001.06  5009.9 2003.32    5019 2007.67
    5025 2009.31  5112.3 2016.53  5127.1 2018.92  5139.4 2022.17  5148.5 2022.42
  5154.4 2024.63  5169.5  2026.2  5175.5 2025.67  5184.6 2026.79  5190.6 2026.03
  5198.9 2027.87  5205.7 2031.66  5211.6 2032.02  5226.7 2037.64  5230.1 2035.84
#Mann= 5 ,-1 , 0
  4683.9     .07       0  4722.3     .16       0  4920.8     .07       0
  4998.5     .07       0  5009.4     .07       0
Bank Sta=4998.5,5009.4
XS Rating Curve= 0 ,0
Exp/Cntr=0.3,0.1

Type RM Length L Ch R = 1 ,18695   ,170,170,170
BEGIN DESCRIPTION:
Bluff Creek 28.0
END DESCRIPTION:
XS GIS Cut Line= 4
      1404222.05      6887093.21        1404305.        6886888.
      1404348.68      6886779.93        1404305.        6886638.
#Sta/Elev= 30
  4662.1 2041.47  4683.6 2040.41  4700.1 2036.13  4731.9 2037.75  4743.2  2034.4
    4754 2033.52  4766.8 2035.14    4795 2030.45  4834.9 2023.35  4915.8 2019.46
  4937.4 2011.88  4969.7 2009.44    4976 2001.53  4985.8 1999.45  4986.3 1998.95
  4996.7 1999.45  4998.3 2001.43  5012.5 2001.97  5028.8 2007.21  5034.1 2002.86
  5043.9 2004.93  5054.3 2009.91  5061.5 2010.73  5066.8 2008.84  5075.3 2013.57
  5094.2 2018.45  5099.5 2014.51  5106.7 2020.01  5135.3  2021.7  5148.5 2021.98
#Mann= 6 ,-1 , 0
  4662.1     .07       0    4795     .16       0  4834.9     .07       0
  4985.8     .07       0  4996.7     .07       0  5135.3     .16       0
Bank Sta=4985.8,4996.7
XS Rating Curve= 0 ,0
Exp/Cntr=0.3,0.1

Type RM Length L Ch R = 1 ,18525   ,328,328,328
BEGIN DESCRIPTION:
Bluff Creek 27.1
END DESCRIPTION:
XS GIS Cut Line= 3
      1404581.94        6887103.      1404499.45      6886833.23
      1404334.25      6886612.13
#Sta/Elev= 30
  4717.9 2038.45  4726.6 2037.74    4754 2038.67  4900.9 2031.62  4911.4 2028.83
  4921.8 2022.35  4933.6 2012.55  4953.2 2010.18  4984.6 2010.22  4999.1 2000.27
  5006.5 1997.53  5014.3  1997.6  5028.9 2001.71  5035.1 2001.15  5043.5 2004.21
  5049.7 1998.65  5064.3 2003.17  5065.1 1997.26  5065.6 1996.76    5076 1997.26
  5078.9 2000.14  5085.1 1997.29  5099.7 1997.96  5114.3 2002.45  5120.6 2002.23
  5135.2 2009.02  5143.5 2014.84  5156.3 2019.06  5263.4 2020.87    5276 2021.29
#Mann= 5 ,-1 , 0
  4717.9     .16       0  4726.6     .07       0  5065.1     .07       0
    5076     .07       0  5263.4     .16       0
Bank Sta=5065.1,5076
XS Rating Curve= 0 ,0
Exp/Cntr=0.3,0.1

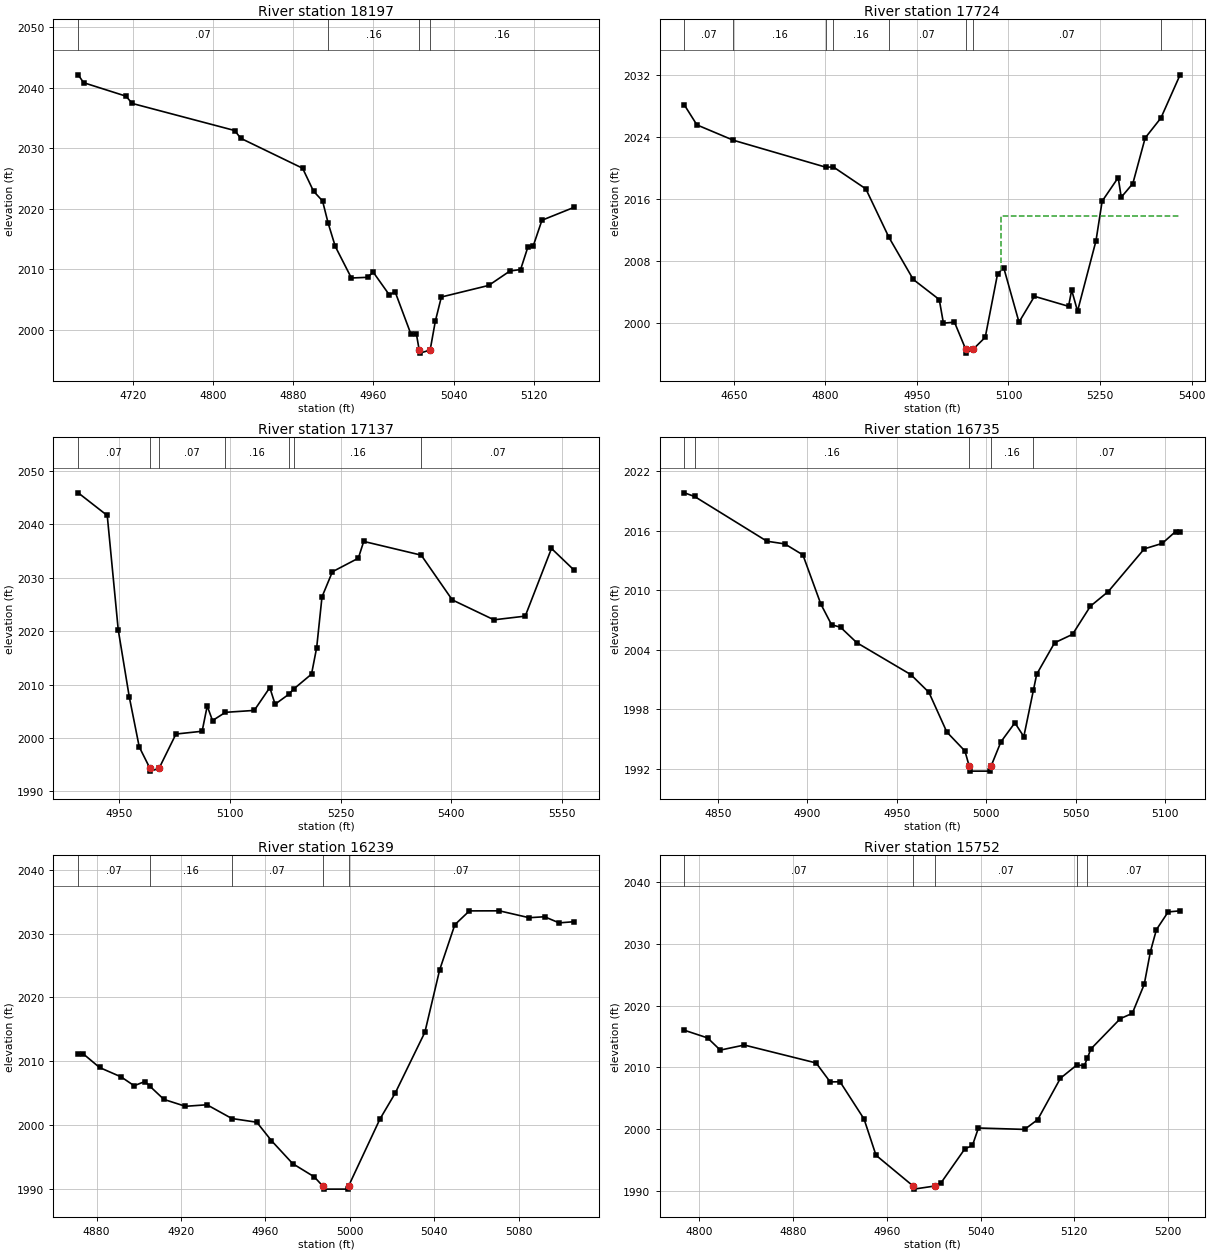
Type RM Length L Ch R = 1 ,18197   ,473,473,473
BEGIN DESCRIPTION:
Bluff Creek 27.0
END DESCRIPTION:
XS GIS Cut Line= 4
      1404725.78      6886773.21        1404605.        6886588.
      1404505.47      6886533.26      1404355.02      6886587.99
#Sta/Elev= 30
  4665.3 2042.15  4670.7 2040.85  4712.9 2038.63  4719.3 2037.42  4821.5 2032.95
  4827.5 2031.67  4889.3 2026.72  4900.2 2022.93  4909.2 2021.32  4914.8 2017.65
  4921.9 2013.81    4938 2008.59  4954.1  2008.7  4959.8 2009.55  4975.9 2005.79
  4981.6 2006.33  4997.4 1999.33  5002.9 1999.33  5005.7 1996.68  5006.2 1996.18
  5016.6 1996.68  5021.8 2001.47  5027.8 2005.45    5075 2007.36  5096.3 2009.75
  5106.9 2009.99  5114.2 2013.72  5119.6 2013.93  5128.2 2018.13  5160.1 2020.25
#Mann= 4 ,-1 , 0
  4665.3     .07       0  4914.8     .16       0  5005.7     .07       0
  5016.6     .16       0
Bank Sta=5005.7,5016.6
XS Rating Curve= 0 ,0
Exp/Cntr=0.3,0.1

Type RM Length L Ch R = 1 ,17724   ,587,587,587
BEGIN DESCRIPTION:
Bluff Creek 26.0
END DESCRIPTION:
XS GIS Cut Line= 3
      1404707.39      6886474.84      1404386.46       6886187.3
      1404008.22      6886140.75
#Sta/Elev= 30
  4569.1 2028.11  4589.6 2025.55  4649.4 2023.57  4800.8  2020.1  4813.1 2020.13
  4866.3 2017.31  4904.1 2011.07    4944 2005.64  4986.6 2003.05  4993.4 2000.01
  5011.5 2000.14  5029.9 1996.65  5030.4 1996.15  5042.1 1996.65  5061.9 1998.19
  5082.1 2006.36  5092.2 2007.15  5117.2 2000.14  5142.5 2003.47  5198.4 2002.18
  5203.5 2004.27  5213.1 2001.56  5243.3 2010.61  5253.4 2015.72  5279.7 2018.76
  5284.7 2016.23  5303.7    2018  5323.9 2023.87  5349.7 2026.44  5381.1    2032
#Mann= 8 ,-1 , 0
  4569.1     .07       0  4649.4     .16       0  4800.8     .07       0
  4813.1     .16       0  4904.1     .07       0  5029.9     .07       0
  5042.1     .07       0  5349.7    .035       0
#XS Ineff= 2 , 0
                         5087.31         2013.77
Permanent Ineff=
       F       F
Bank Sta=5029.9,5042.1
XS Rating Curve= 0 ,0
Exp/Cntr=0.3,0.1

Type RM Length L Ch R = 1 ,17137   ,402,402,402
BEGIN DESCRIPTION:
Bluff Creek 25.0
END DESCRIPTION:
XS GIS Cut Line= 3
      1404971.68      6886366.33      1404911.75       6886278.9
      1404503.56      6885886.22
#Sta/Elev= 30
    4894 2045.87  4933.4 2041.63  4948.3 2020.25  4963.2 2007.75  4976.8 1998.33
  4991.4  1994.3  4991.9  1993.8  5003.6  1994.3  5026.6 2000.74  5062.1 2001.26
    5069 2005.98  5076.2 2003.26  5093.7  2004.8  5132.8 2005.16  5153.9 2009.43
  5161.1 2006.32  5179.3 2008.14  5186.3 2009.16  5210.5 2011.95  5217.5 2016.92
  5224.7  2026.4  5238.8  2031.1    5274 2033.64  5281.3 2036.78  5359.3 2034.21
  5401.4 2025.84    5458 2022.11  5500.4  2022.8    5536 2035.46  5566.4 2031.44
#Mann= 7 ,-1 , 0
    4894     .07       0  4991.4     .07       0  5003.6     .07       0
  5093.7     .16       0  5179.3     .07       0  5186.3     .16       0
  5359.3     .07       0
Bank Sta=4991.4,5003.6
XS Rating Curve= 0 ,0
Exp/Cntr=0.3,0.1

Type RM Length L Ch R = 1 ,16735   ,496,496,496
BEGIN DESCRIPTION:
Bluff Creek 24.0
END DESCRIPTION:
XS GIS Cut Line= 3
      1405180.82       6885961.7      1405013.14      6885944.06
      1404905.01        6885938.
#Sta/Elev= 30
  4831.4 2019.84  4837.1 2019.47  4877.5 2014.96  4887.5 2014.69  4897.6 2013.58
  4907.6 2008.63  4913.6 2006.54  4918.6 2006.29  4927.7 2004.73  4957.9 2001.51
    4968 1999.72    4978 1995.72  4988.1 1993.81  4990.5 1992.28    4991 1991.78
  5002.2 1991.78  5002.7 1992.28  5008.2 1994.73    5016 1996.65    5021 1995.26
  5026.4 1999.98  5028.2 2001.55  5038.2 2004.72  5048.2 2005.57  5058.2 2008.41
  5068.2 2009.89  5088.3 2014.19  5098.3 2014.74  5105.8 2015.94  5108.3 2015.94
#Mann= 5 ,-1 , 0
  4831.4     .07       0  4837.1     .16       0  4990.5     .07       0
  5002.7     .16       0  5026.4     .07       0
Bank Sta=4990.5,5002.7
XS Rating Curve= 0 ,0
Exp/Cntr=0.3,0.1

Type RM Length L Ch R = 1 ,16239   ,487,487,487
BEGIN DESCRIPTION:
Bluff Creek 23.0
END DESCRIPTION:
XS GIS Cut Line= 3
      1405254.99      6885687.96      1405231.69      6885561.39
      1405155.03      6885488.03
#Sta/Elev= 30
  4871.3 2011.11  4873.8 2011.11  4881.4    2009  4891.6 2007.53  4897.8 2006.14
  4902.9  2006.8  4905.2 2006.08  4911.9 2003.99  4922.1 2002.91  4932.3 2003.15
  4944.1 2000.99  4955.9 2000.41  4962.8 1997.53  4972.9 1993.91  4983.1 1991.84
  4987.1 1990.41  4987.6 1989.91  4998.9 1989.91  4999.4 1990.41  5014.2 2000.89
  5021.4 2004.94  5035.5 2014.52  5042.5 2024.31  5049.7 2031.41  5056.6 2033.58
  5070.8 2033.59  5084.9 2032.51  5092.2 2032.66  5099.1  2031.7  5106.1 2031.88
#Mann= 5 ,-1 , 0
  4871.3     .07       0  4905.2     .16       0  4944.1     .07       0
  4987.1     .07       0  4999.4     .07       0
Bank Sta=4987.1,4999.4
XS Rating Curve= 0 ,0
Exp/Cntr=0.3,0.1

Type RM Length L Ch R = 1 ,15752   ,496,496,496
BEGIN DESCRIPTION:
Bluff Creek 22.0
END DESCRIPTION:
XS GIS Cut Line= 3
        1405655.      6885487.98      1405611.07      6885279.87
      1405404.98        6885238.
#Sta/Elev= 30
  4787.3 2016.02  4807.1 2014.78  4817.9 2012.81  4838.4 2013.63  4899.7 2010.73
  4911.7 2007.66  4920.1 2007.69  4940.6 2001.66  4950.8  1995.8  4982.5 1990.82
    4983 1990.32  5000.9 1990.82  5006.2 1991.31  5026.6 1996.83  5033.1 1997.39
  5038.2 2000.21  5077.6 1999.98  5088.8 2001.57  5108.2 2008.26  5122.1 2010.39
  5128.6 2010.29  5131.2 2011.54  5134.3 2013.02  5159.3  2017.9  5169.5 2018.75
  5179.7 2023.45    5185 2028.76  5190.1  2032.3  5200.1 2035.16  5210.3 2035.34
#Mann= 5 ,-1 , 0
  4787.3     .07       0  4982.5     .07       0  5000.9     .07       0
  5122.1     .16       0  5131.2     .07       0
Bank Sta=4982.5,5000.9
XS Rating Curve= 0 ,0
Exp/Cntr=0.3,0.1

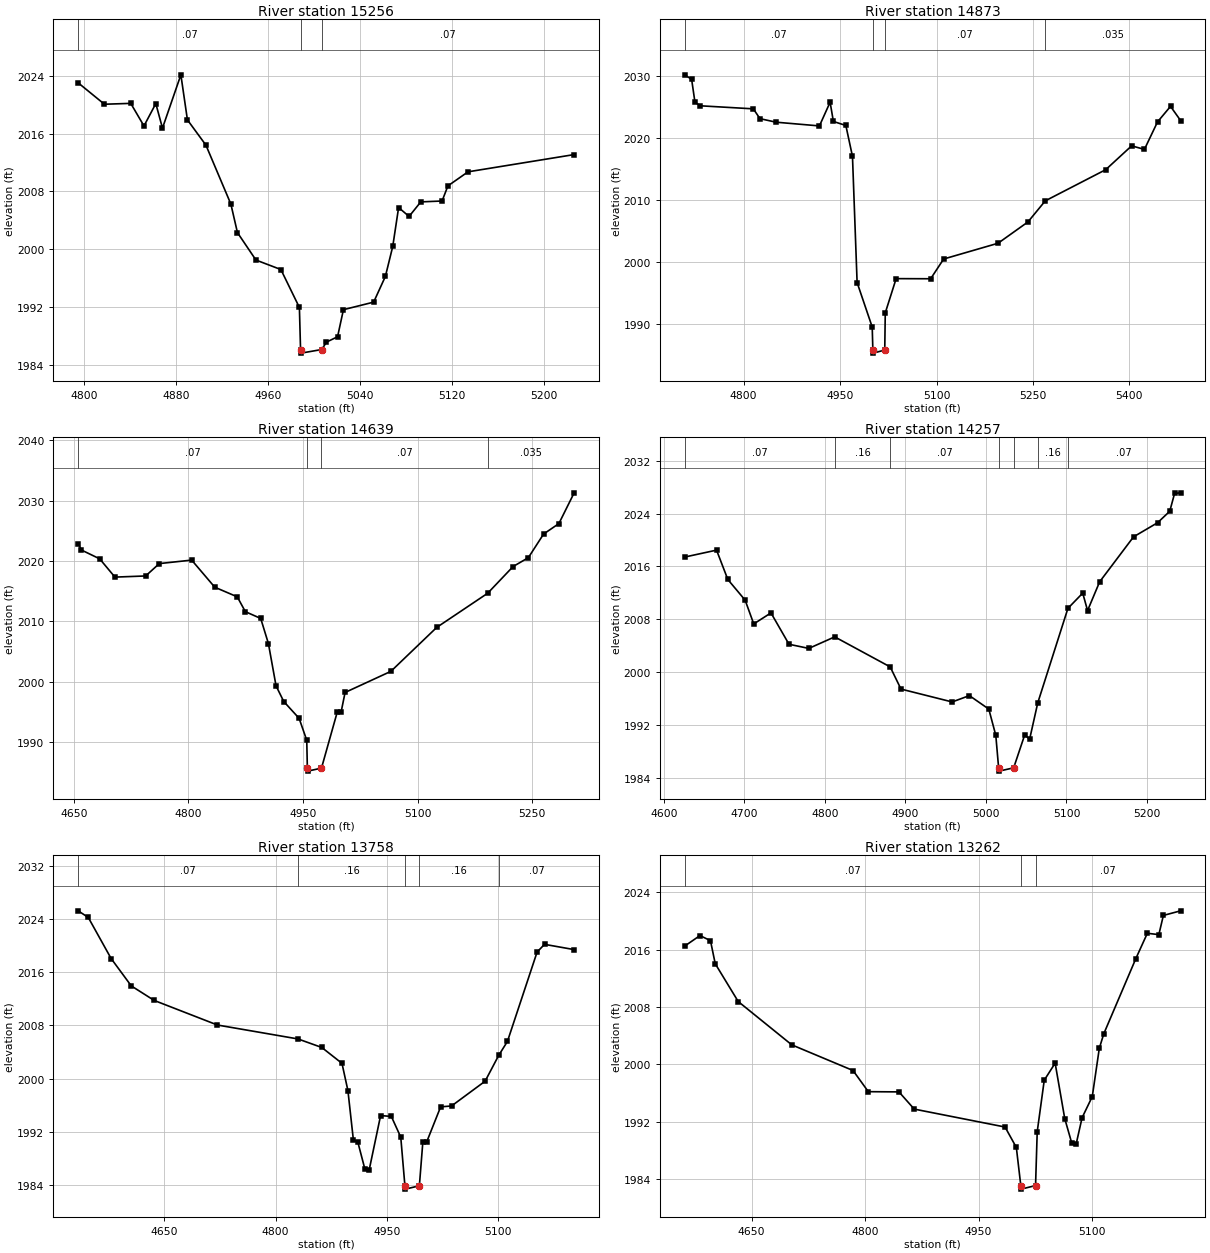
Type RM Length L Ch R = 1 ,15256   ,383,383,383
BEGIN DESCRIPTION:
Bluff Creek 21.0
END DESCRIPTION:
XS GIS Cut Line= 3
      1406154.98      6885087.99      1405975.27      6884988.52
      1405754.99        6884938.
#Sta/Elev= 30
  4794.6 2022.99  4817.4 2020.04  4840.3 2020.16  4851.8 2017.04  4862.1 2020.13
  4867.9 2016.74  4883.9  2024.1  4889.6 2017.88  4905.7 2014.39  4927.4 2006.25
  4933.1 2002.32  4949.2 1998.53  4970.9 1997.22    4987 1991.98    4988 1986.18
  4988.5 1985.68  5006.5 1986.18  5010.5  1987.2  5020.2 1987.94  5025.3 1991.68
  5051.6 1992.72  5061.8 1996.27  5068.2 2000.41  5073.3 2005.78  5082.4 2004.55
  5092.6 2006.56  5111.1 2006.68  5116.2 2008.77  5133.7 2010.71    5226 2013.09
#Mann= 3 ,-1 , 0
  4794.6     .07       0    4988     .07       0  5006.5     .07       0
Bank Sta=4988,5006.5
XS Rating Curve= 0 ,0
Exp/Cntr=0.3,0.1

Type RM Length L Ch R = 1 ,14873   ,234,234,234
BEGIN DESCRIPTION:
Bluff Creek 20.1
END DESCRIPTION:
XS GIS Cut Line= 3
      1406438.84      6884755.92      1406155.16        6884688.
      1405679.43      6884626.37
#Sta/Elev= 30
  4708.3 2030.12  4719.1  2029.4  4724.3 2025.69  4732.8 2025.13  4815.1 2024.64
  4825.4 2023.06  4850.4 2022.49  4917.9 2021.89  4934.5 2025.71  4939.6 2022.61
    4959 2021.96  4969.3 2016.98  4976.5 1996.66    5000 1989.49    5001 1985.79
  5001.5 1985.29  5019.5 1985.79  5020.3 1991.77  5037.2 1997.29  5090.9 1997.27
  5111.1 2000.45  5195.7 2002.99  5242.2 2006.42  5269.2 2009.82  5363.2 2014.84
  5403.5 2018.68  5423.4 2018.11  5443.8 2022.54    5464 2025.04  5479.7 2022.75
#Mann= 4 ,-1 , 0
  4708.3     .07       0    5001     .07       0  5019.5     .07       0
  5269.2    .035       0
Bank Sta=5001,5019.5
XS Rating Curve= 0 ,0
Exp/Cntr=0.3,0.1

Type RM Length L Ch R = 1 ,14639   ,382,382,382
BEGIN DESCRIPTION:
Bluff Creek 20.0
END DESCRIPTION:
XS GIS Cut Line= 3
      1406402.92      6884523.53      1406060.13      6884490.28
      1405755.04        6884488.
#Sta/Elev= 30
  4655.6 2022.86  4659.8  2021.8  4683.7 2020.34  4703.7 2017.31  4743.9  2017.5
  4761.8 2019.55  4804.2 2020.13  4834.4 2015.64  4863.9 2014.04  4874.5 2011.58
  4894.6 2010.46  4904.7 2006.29  4914.7 1999.28  4924.8 1996.69  4944.9  1993.9
  4954.9 1990.26  4955.7 1985.65  4956.2 1985.15  4974.2 1985.65    4995 1995.01
    5000 1995.01  5005.1 1998.19  5065.1 2001.69  5125.1 2008.97  5191.9 2014.64
  5225.1 2019.06  5245.1 2020.53  5265.1 2024.45  5285.1 2026.18  5305.1 2031.28
#Mann= 4 ,-1 , 0
  4655.6     .07       0  4955.7     .07       0  4974.2     .07       0
  5191.9    .035       0
Bank Sta=4955.7,4974.2
XS Rating Curve= 0 ,0
Exp/Cntr=0.3,0.1

Type RM Length L Ch R = 1 ,14257   ,499,499,499
BEGIN DESCRIPTION:
Bluff Creek 19.0
END DESCRIPTION:
XS GIS Cut Line= 3
      1406455.04      6884288.01      1406105.81      6884153.33
      1405904.99      6884288.01
#Sta/Elev= 30
  4625.7 2017.42  4665.3 2018.47  4679.3 2014.02  4700.8 2010.89  4711.5 2007.29
  4732.9 2008.96  4755.3 2004.21  4779.9 2003.58  4812.1 2005.33    4881 2000.78
  4894.4 1997.42    4958 1995.47  4979.4 1996.43  5003.5 1994.39  5012.2 1990.41
  5015.7 1985.49  5016.2 1984.99  5034.4 1985.49  5048.2 1990.51  5054.2 1989.81
  5064.3 1995.32  5101.8 2009.65  5120.2 2011.96  5126.2 2009.31  5141.2 2013.67
  5183.3 2020.48  5213.3 2022.63  5228.3 2024.36  5234.3 2027.06  5241.8 2027.15
#Mann= 7 ,-1 , 0
  4625.7     .07       0  4812.1     .16       0    4881     .07       0
  5015.7     .07       0  5034.4     .07       0  5064.3     .16       0
  5101.8     .07       0
Bank Sta=5015.7,5034.4
XS Rating Curve= 0 ,0
Exp/Cntr=0.3,0.1

Type RM Length L Ch R = 1 ,13758   ,496,496,496
BEGIN DESCRIPTION:
Bluff Creek 18.0
END DESCRIPTION:
XS GIS Cut Line= 3
      1406805.02      6884038.01       1406407.7      6883794.12
      1406204.99        6883788.
#Sta/Elev= 30
  4533.8  2025.2  4547.4  2024.2  4578.2 2018.04  4605.4 2013.93  4636.3 2011.75
  4721.6 2008.06  4830.3 2005.97  4862.4 2004.69  4889.6 2002.31  4897.6 1998.23
    4905  1990.8  4910.9 1990.53  4920.4 1986.48  4926.3 1986.31  4941.7 1994.47
  4956.2 1994.34  4968.9 1991.23  4974.5 1983.93    4975 1983.43    4994 1983.93
  4998.7 1990.52  5003.9 1990.52  5022.7 1995.78  5037.4 1995.91  5082.7 1999.63
  5101.1 2003.52  5112.8  2005.6  5152.8 2019.01  5162.8 2020.17  5202.8 2019.38
#Mann= 5 ,-1 , 0
  4533.8     .07       0  4830.3     .16       0  4974.5     .07       0
    4994     .16       0  5101.1     .07       0
Bank Sta=4974.5,4994
XS Rating Curve= 0 ,0
Exp/Cntr=0.3,0.1

Type RM Length L Ch R = 1 ,13262   ,492,492,492
BEGIN DESCRIPTION:
Bluff Creek 17.0
END DESCRIPTION:
XS GIS Cut Line= 3
      1407004.96      6883437.99      1406571.57      6883371.29
      1406455.01      6883188.01
#Sta/Elev= 30
  4561.5 2016.48  4581.7 2017.95  4595.6 2017.24  4601.9 2014.02  4632.3 2008.75
  4703.1 2002.71  4784.1 1999.13  4804.3 1996.18  4844.8 1996.15    4865 1993.75
  4985.1 1991.25    5000  1988.4  5005.9 1983.09  5006.4 1982.59  5025.4 1983.09
  5027.6 1990.59  5036.9 1997.78  5051.3 2000.16    5064 1992.43  5073.3    1989
  5079.2 1988.93  5086.9 1992.54  5100.4  1995.5  5109.7 2002.23  5115.6 2004.25
    5158 2014.74  5173.2 2018.27  5188.4 2018.08  5194.4 2020.76  5217.2  2021.4
#Mann= 3 ,-1 , 0
  4561.5     .07       0  5005.9     .07       0  5025.4     .07       0
Bank Sta=5005.9,5025.4
XS Rating Curve= 0 ,0
Exp/Cntr=0.3,0.1

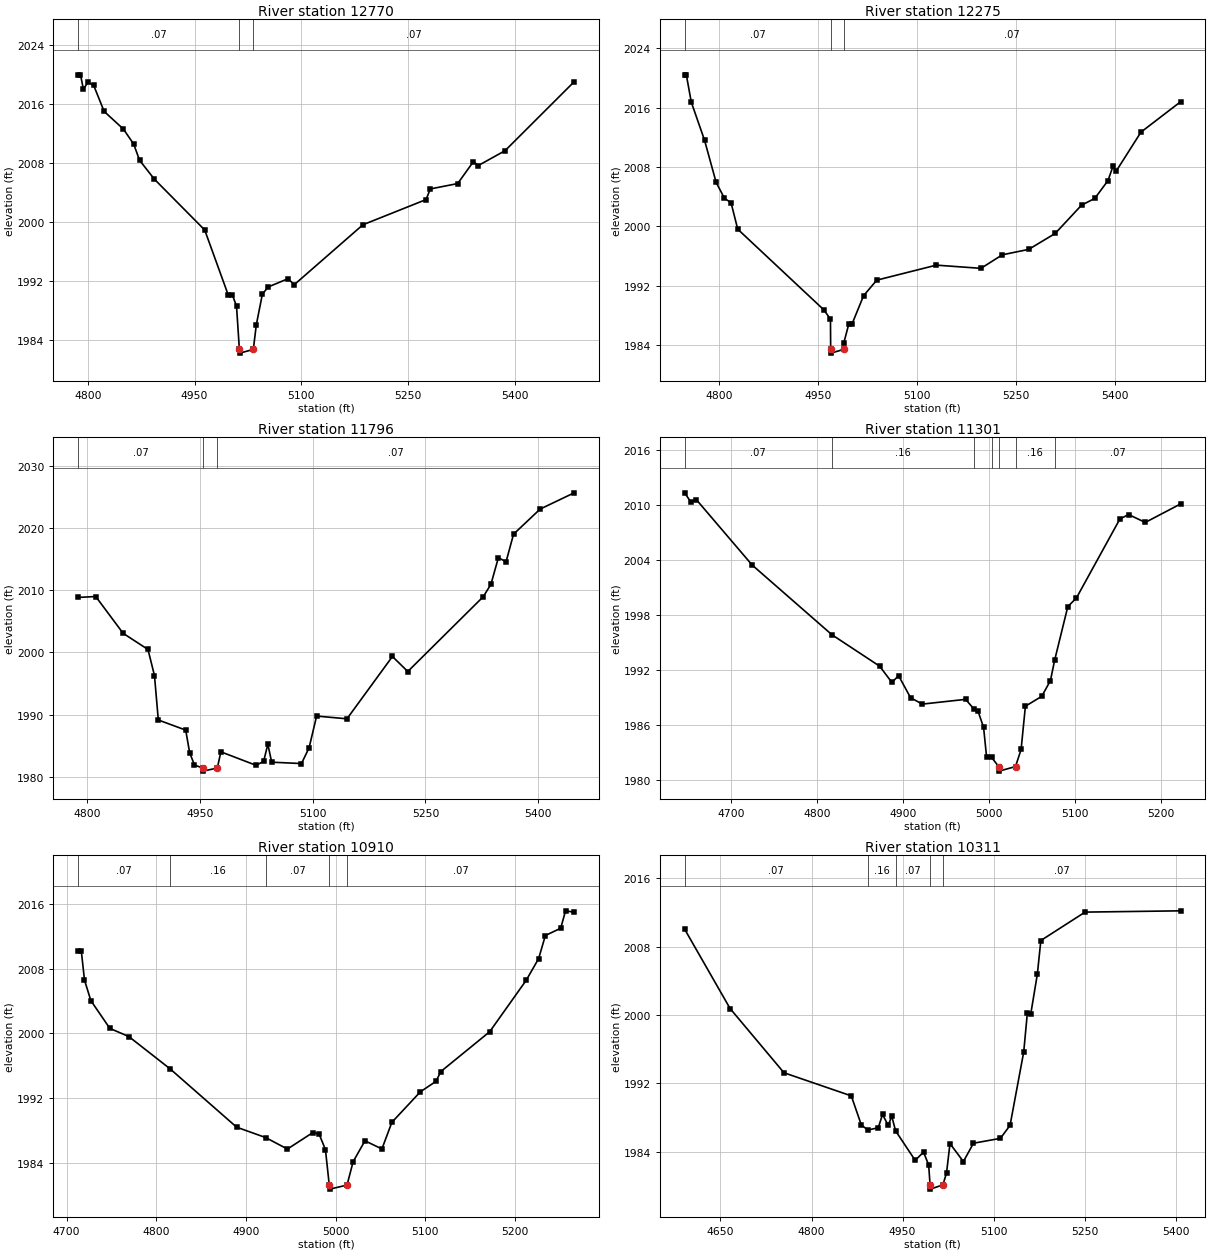
Type RM Length L Ch R = 1 ,12770   ,495,495,495
BEGIN DESCRIPTION:
Bluff Creek 16.0
END DESCRIPTION:
XS GIS Cut Line= 3
      1407155.02      6883288.02      1406985.23      6883158.41
        1406555.        6882938.
#Sta/Elev= 30
  4786.4 2019.93  4789.6 2019.93  4793.7 2017.98    4800 2018.91  4808.2 2018.49
  4822.8 2014.97  4849.9 2012.57  4864.4 2010.53  4872.6 2008.34  4893.5 2005.77
  4964.2 1998.88    4997 1990.13  5002.9 1990.13  5008.9 1988.54  5012.9 1982.68
  5013.4 1982.18  5032.5 1982.68  5036.7 1986.02  5045.2 1990.17  5053.3 1991.15
  5081.1 1992.27  5090.1 1991.47  5186.5 1999.59  5275.3 2003.01  5281.2 2004.45
  5319.7 2005.18  5341.9 2008.17  5348.6 2007.62  5386.3 2009.64  5483.4 2018.99
#Mann= 3 ,-1 , 0
  4786.4     .07       0  5012.9     .07       0  5032.5     .07       0
Bank Sta=5012.9,5032.5
XS Rating Curve= 0 ,0
Exp/Cntr=0.3,0.1

Type RM Length L Ch R = 1 ,12275   ,479,479,479
BEGIN DESCRIPTION:
Bluff Creek 15.0
END DESCRIPTION:
XS GIS Cut Line= 3
      1407354.95        6882788.       1407104.6        6882763.
      1406605.02        6882788.
#Sta/Elev= 30
  4748.4 2020.41  4750.9 2020.41  4758.4 2016.74  4778.5 2011.61  4796.1 2005.93
  4808.7  2003.8  4818.7  2003.2  4828.8 1999.64  4959.4 1988.78  4969.4 1987.53
  4969.7 1983.46  4970.2 1982.96  4989.3 1983.46  4989.5 1984.29  4997.3 1986.92
  5002.3 1986.92  5019.6 1990.69  5039.6 1992.78  5129.8  1994.8  5197.5 1994.37
  5229.9 1996.19  5269.9 1996.92    5310 1999.06    5350 2002.87  5370.1 2003.78
  5390.1 2006.18  5397.6 2008.08  5402.6 2007.46  5440.1  2012.7  5500.2 2016.79
#Mann= 3 ,-1 , 0
  4748.4     .07       0  4969.7     .07       0  4989.3     .07       0
Bank Sta=4969.7,4989.3
XS Rating Curve= 0 ,0
Exp/Cntr=0.3,0.1

Type RM Length L Ch R = 1 ,11796   ,495,495,495
BEGIN DESCRIPTION:
Bluff Creek 14.0
END DESCRIPTION:
XS GIS Cut Line= 3
      1407154.98        6882388.      1406949.79      6882438.43
      1406505.04        6882488.
#Sta/Elev= 30
  4788.7 2008.87    4812 2009.01  4848.4 2003.08  4881.4 2000.48    4890 1996.28
  4895.1 1989.12  4931.5 1987.49  4936.7 1983.87  4943.1 1981.87  4953.9 1981.38
  4954.4 1980.88  4973.5 1981.38  4978.2 1983.99  5024.9 1981.82    5035 1982.45
  5040.6 1985.22  5045.7 1982.32  5085.3  1982.1  5095.4 1984.65  5105.4 1989.75
  5145.7 1989.31  5206.1 1999.35  5226.5 1996.93  5326.8 2008.99  5336.9 2010.97
  5346.9 2015.29    5357 2014.59    5367 2019.06  5402.3  2023.1  5447.5 2025.72
#Mann= 3 ,-1 , 0
  4788.7     .07       0  4953.9     .07       0  4973.5     .07       0
Bank Sta=4953.9,4973.5
XS Rating Curve= 0 ,0
Exp/Cntr=0.3,0.1

Type RM Length L Ch R = 1 ,11301   ,391,391,391
BEGIN DESCRIPTION:
Bluff Creek 13.0
END DESCRIPTION:
XS GIS Cut Line= 3
      1407254.99      6882337.99      1407025.38      6882068.16
      1406805.04        6882038.
#Sta/Elev= 30
  4645.7 2011.29  4652.8 2010.29  4659.4 2010.53  4724.2 2003.41  4816.9 1995.81
  4872.4 1992.38  4886.7  1990.6  4894.4 1991.35  4908.3 1988.95  4921.9 1988.24
  4972.4 1988.76  4982.4 1987.67  4986.7 1987.51  4993.3 1985.69  4996.8 1982.44
  5002.5 1982.44  5010.8 1981.43  5011.3 1980.93  5030.4 1981.43  5036.9 1983.29
  5041.9 1988.01  5060.9 1989.09    5071  1990.8  5075.9 1993.03  5091.2 1998.87
  5101.3 1999.83  5151.8 2008.44  5161.9 2008.92  5181.3 2008.06  5222.4 2010.08
#Mann= 7 ,-1 , 0
  4645.7     .07       0  4816.9     .16       0  4982.4     .07       0
  5002.5     .16       0  5010.8     .07       0  5030.4     .16       0
  5075.9     .07       0
Bank Sta=5010.8,5030.4
XS Rating Curve= 0 ,0
Exp/Cntr=0.3,0.1

Type RM Length L Ch R = 1 ,10910   ,599,599,599
BEGIN DESCRIPTION:
Bluff Creek 12.0
END DESCRIPTION:
XS GIS Cut Line= 3
      1407504.97      6882037.97      1407303.26      6881833.81
      1407055.01        6881738.
#Sta/Elev= 30
    4713 2010.13  4716.5 2010.13    4720 2006.59  4727.1 2004.05  4748.3 2000.62
  4769.5 1999.61  4815.4 1995.63  4889.7 1988.42    4922 1987.14  4946.3 1985.72
  4974.6 1987.75  4981.6 1987.58  4988.7 1985.66    4993 1981.27  4993.5 1980.77
  5012.8 1981.27  5019.6 1984.16  5032.8 1986.74  5051.7 1985.73  5062.8 1989.02
  5094.6 1992.79    5112 1994.08  5117.4 1995.29  5171.9 2000.21  5212.5 2006.54
  5226.5 2009.24    5234 2012.09  5251.1 2012.99  5256.5 2015.14  5266.1 2014.97
#Mann= 5 ,-1 , 0
    4713     .07       0  4815.4     .16       0    4922     .07       0
    4993     .07       0  5012.8     .07       0
Bank Sta=4993,5012.8
XS Rating Curve= 0 ,0
Exp/Cntr=0.3,0.1

Type RM Length L Ch R = 1 ,10311   ,599,599,599
BEGIN DESCRIPTION:
Bluff Creek 11.0
END DESCRIPTION:
XS GIS Cut Line= 3
      1408054.99      6881687.99      1407691.17      6881501.13
      1407504.99      6881137.98
#Sta/Elev= 30
    4591 2010.05  4665.8 2000.76  4754.6 1993.23  4865.5 1990.52  4882.1  1987.1
  4892.9 1986.52  4909.9 1986.78    4917 1988.34  4926.4 1987.05  4932.1 1988.15
  4938.5 1986.42  4970.8 1982.96  4984.5 1983.93    4993 1982.42  4995.3 1980.09
  4995.8 1979.59  5016.4 1980.09  5022.4 1981.47  5028.1 1984.93  5050.2 1982.82
  5066.8 1984.97  5111.2 1985.54  5127.1 1987.07  5149.6 1995.67  5155.6 2000.25
  5161.2 2000.12  5172.1 2004.81  5177.8 2008.73  5250.7 2012.06  5408.1 2012.21
#Mann= 5 ,-1 , 0
    4591     .07       0  4892.9     .16       0  4938.5     .07       0
  4995.3     .07       0  5016.4     .07       0
Bank Sta=4995.3,5016.4
XS Rating Curve= 0 ,0
Exp/Cntr=0.3,0.1