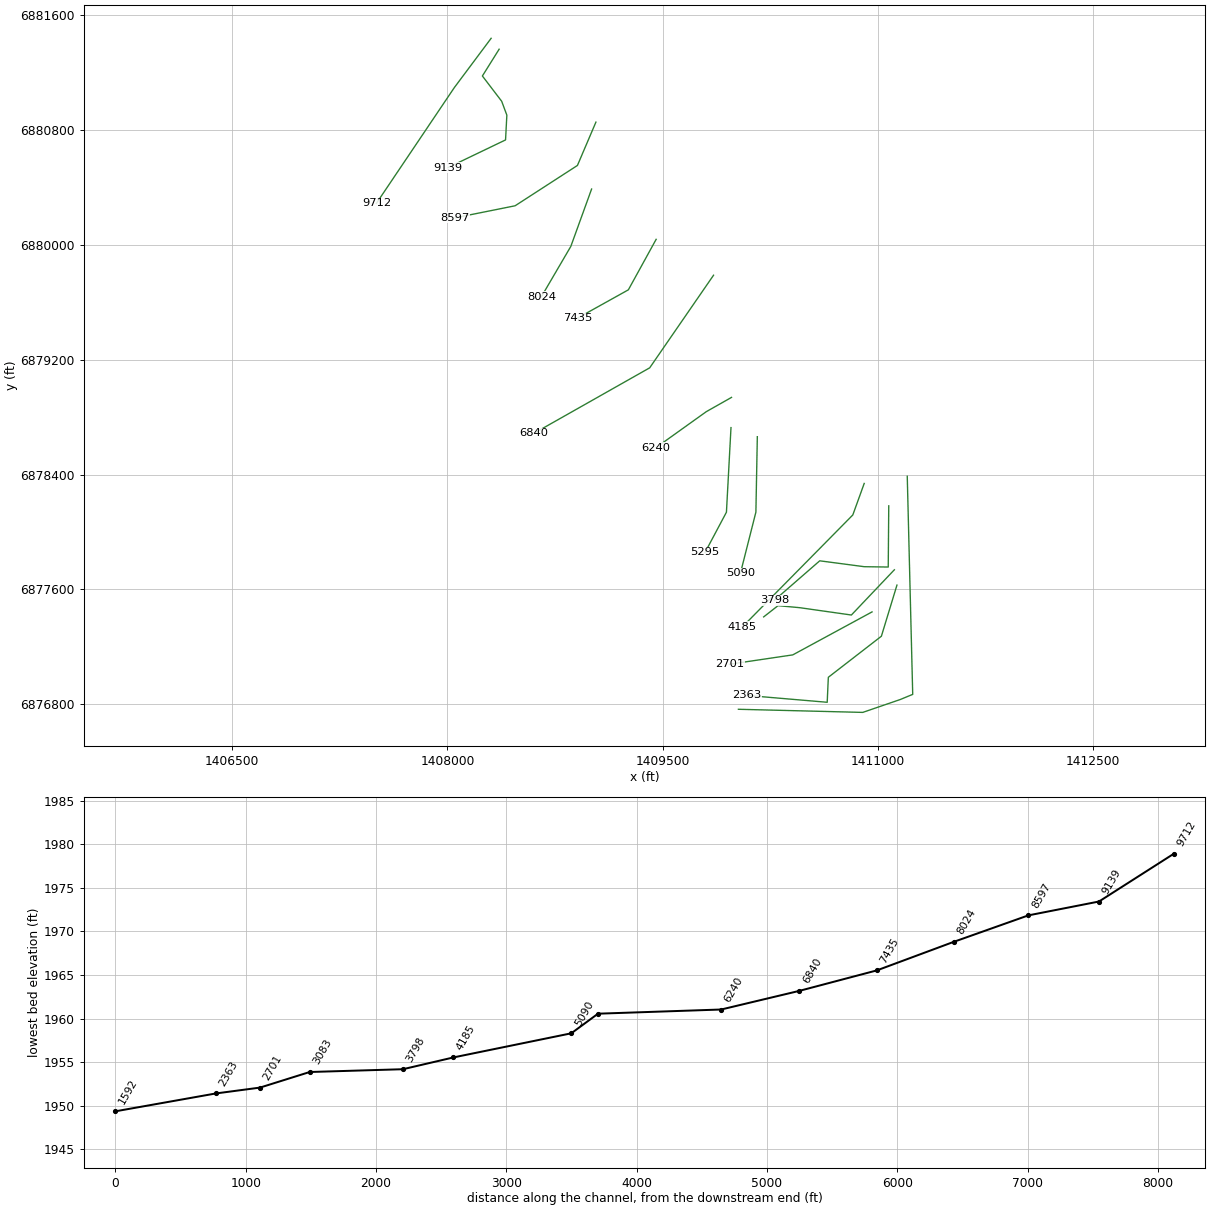
HEC-RAS study Bluff Creek.prj: Bluff Creek Base Level Engineering

--- Bluff Creek.g01 (geometry) --- (continued)

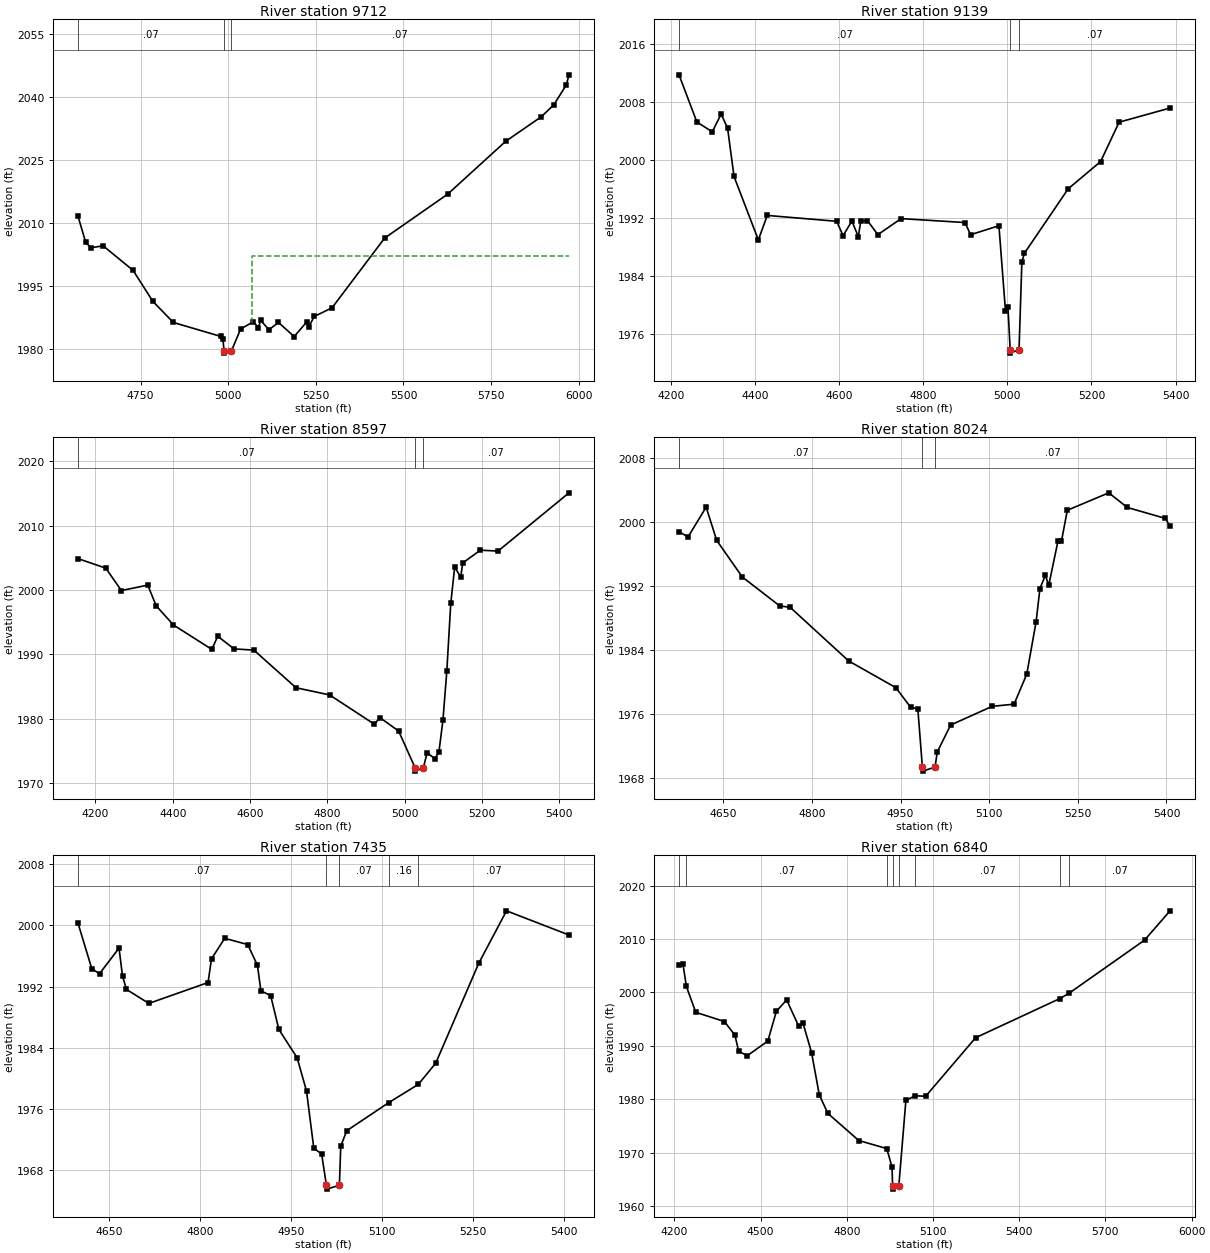
Type RM Length L Ch R = 1 ,9712    ,573,573,573
BEGIN DESCRIPTION:
Bluff Creek 10.0
END DESCRIPTION:
XS GIS Cut Line= 3
      1408304.98      6881437.98      1408048.27      6881094.51
      1407505.01      6880288.02
#Sta/Elev= 30
  4571.2 2011.53  4593.1 2005.34  4607.7 2004.01  4643.1 2004.45  4728.5 1998.61
  4784.8 1991.24  4843.2 1986.21  4978.7 1982.88  4984.9 1982.33    4988  1979.4
  4988.5  1978.9  5009.1  1979.4  5035.3 1984.64  5071.3 1986.36  5086.3    1985
  5092.3 1986.71  5116.3 1984.46  5143.3 1986.21  5188.2 1982.85  5224.2 1986.35
  5230.3  1985.2  5245.2 1987.63  5296.2 1989.69  5446.2 2006.29  5626.1 2016.76
  5791.6 2029.34    5893 2035.18  5928.9 2038.03  5964.9  2042.8  5972.4 2045.19
#Mann= 3 ,-1 , 0
  4571.2     .07       0    4988     .07       0  5009.1     .07       0
#XS Ineff= 2 , 0
                         5067.71         2001.97
Permanent Ineff=
       F       F
Bank Sta=4988,5009.1
XS Rating Curve= 0 ,0
Exp/Cntr=0.3,0.1

Type RM Length L Ch R = 1 ,9139    ,542,542,542
BEGIN DESCRIPTION:
Bluff Creek 9.0
END DESCRIPTION:
XS GIS Cut Line= 6
      1408360.66      6881361.91      1408243.97      6881175.46
      1408378.43      6880999.35      1408414.41      6880902.77
      1408405.37      6880730.18      1408005.01        6880538.
#Sta/Elev= 30
  4219.3 2011.81  4261.7 2005.31  4298.3 2003.95  4319.5  2006.4  4334.8 2004.45
  4350.1 1997.79  4407.9 1989.04  4429.1 1992.42  4594.2 1991.61  4609.4 1989.63
  4630.4 1991.64  4645.6  1989.5  4651.5 1991.61  4667.1 1991.72  4692.1 1989.77
  4747.4 1991.98  4899.2 1991.44  4912.7 1989.76    4980    1991  4995.6 1979.22
  5001.4 1979.79  5006.7 1973.93  5007.2 1973.43  5027.8 1973.93  5034.6 1985.99
  5040.2 1987.17  5144.7 1996.09  5221.8 1999.85  5265.8 2005.28  5386.9 2007.23
#Mann= 3 ,-1 , 0
  4219.3     .07       0  5006.7     .07       0  5027.8     .07       0
Bank Sta=5006.7,5027.8
XS Rating Curve= 0 ,0
Exp/Cntr=0.3,0.1

Type RM Length L Ch R = 1 ,8597    ,573,573,573
BEGIN DESCRIPTION:
Bluff Creek 8.0
END DESCRIPTION:
XS GIS Cut Line= 4
      1409035.13      6880854.06      1408906.35      6880552.43
      1408471.93      6880271.52      1408055.01        6880188.
#Sta/Elev= 30
  4154.7 2004.89  4226.5 2003.41  4267.1 1999.92  4335.3 2000.77    4357 1997.56
  4401.5 1994.58  4501.1 1990.77  4516.3 1992.82  4558.5 1990.85  4609.9 1990.66
  4718.8 1984.81  4805.8 1983.69  4921.3 1979.15  4936.4 1980.15  4984.6 1978.06
  5027.1 1972.34  5027.6 1971.84  5048.3 1972.34  5058.1 1974.69  5078.5 1973.76
  5088.7 1974.84  5099.1 1979.78  5109.1 1987.41  5119.3 1997.92  5129.5 2003.59
    5145 2001.99  5150.1 2004.21  5195.9  2006.2  5241.6 2006.06  5425.2 2015.12
#Mann= 3 ,-1 , 0
  4154.7     .07       0  5027.1     .07       0  5048.3     .07       0
Bank Sta=5027.1,5048.3
XS Rating Curve= 0 ,0
Exp/Cntr=0.3,0.1

Type RM Length L Ch R = 1 ,8024    ,589,589,589
BEGIN DESCRIPTION:
Bluff Creek 7.0
END DESCRIPTION:
XS GIS Cut Line= 3
        1409005.        6880388.      1408860.18      6879988.44
      1408654.99      6879637.99
#Sta/Elev= 30
    4575 1998.72  4590.3 1998.08  4620.9  2001.8  4638.8 1997.64  4682.2 1993.06
  4745.2 1989.47  4763.4 1989.26  4862.2 1982.57  4941.9 1979.24  4967.2 1976.77
  4979.2  1976.6  4986.9  1969.3  4987.4  1968.8  5008.3  1969.3  5012.1 1971.19
  5034.7 1974.56    5105  1976.9  5142.1 1977.17  5163.6 1980.93  5179.3 1987.43
  5185.9 1991.62    5195 1993.28  5200.8 1992.04  5216.5 1997.59  5222.3 1997.53
  5232.2 2001.41  5302.4 2003.59  5333.8 2001.76  5398.2 2000.39  5406.1  1999.4
#Mann= 3 ,-1 , 0
    4575     .07       0  4986.9     .07       0  5008.3     .07       0
Bank Sta=4986.9,5008.3
XS Rating Curve= 0 ,0
Exp/Cntr=0.3,0.1

Type RM Length L Ch R = 1 ,7435    ,595,595,595
BEGIN DESCRIPTION:
Bluff Creek 6.0
END DESCRIPTION:
XS GIS Cut Line= 3
        1409455.      6880037.99      1409261.27      6879686.21
      1408904.99        6879488.
#Sta/Elev= 30
  4598.4  2000.3  4621.2 1994.33  4633.9 1993.68  4666.1 1997.03  4671.8 1993.38
  4678.3 1991.63  4715.3  1989.8  4812.8 1992.53  4818.5 1995.63  4840.3 1998.31
  4878.2 1997.49  4894.2 1994.78  4899.9 1991.44    4916 1990.83  4929.5  1986.4
  4959.6  1982.7  4975.1 1978.35  4987.1 1970.87    5000 1970.13  5007.9 1966.03
  5008.4 1965.53  5029.3 1966.03  5031.5 1971.16  5041.5 1973.17  5110.3 1976.82
  5159.4 1979.22  5188.1    1982    5259 1995.05  5304.7  2001.9  5407.7 1998.74
#Mann= 5 ,-1 , 0
  4598.4     .07       0  5007.9     .07       0  5029.3     .07       0
  5110.3     .16       0  5159.4     .07       0
Bank Sta=5007.9,5029.3
XS Rating Curve= 0 ,0
Exp/Cntr=0.3,0.1

Type RM Length L Ch R = 1 ,6840    ,600,600,600
BEGIN DESCRIPTION:
Bluff Creek 5.0
END DESCRIPTION:
XS GIS Cut Line= 3
      1409854.98      6879787.97      1409410.03      6879143.08
      1408604.96      6878687.98
#Sta/Elev= 30
  4216.5 2005.09    4230 2005.34  4242.2 2001.11  4274.6 1996.28  4374.4 1994.55
  4410.9 1992.01    4424 1988.99  4453.8 1988.15  4525.4 1990.89  4555.2 1996.47
    4591 1998.59  4632.9 1993.68  4647.8 1994.26  4677.6 1988.74  4704.6 1980.81
  4734.4 1977.35  4841.9 1972.28  4939.3 1970.77  4957.6  1967.3  4959.6 1963.68
  4960.1 1963.18    4981 1963.68  5005.8  1979.8  5038.4 1980.65  5074.7 1980.57
  5248.4 1991.52  5540.4 1998.82  5572.8 1999.82    5836 2009.78  5924.8 2015.27
#Mann= 8 ,-1 , 0
  4216.5    .035       0  4242.2     .07       0  4939.3     .16       0
  4959.6     .07       0    4981     .16       0  5038.4     .07       0
  5540.4     .16       0  5572.8     .07       0
Bank Sta=4959.6,4981
XS Rating Curve= 0 ,0
Exp/Cntr=0.3,0.1

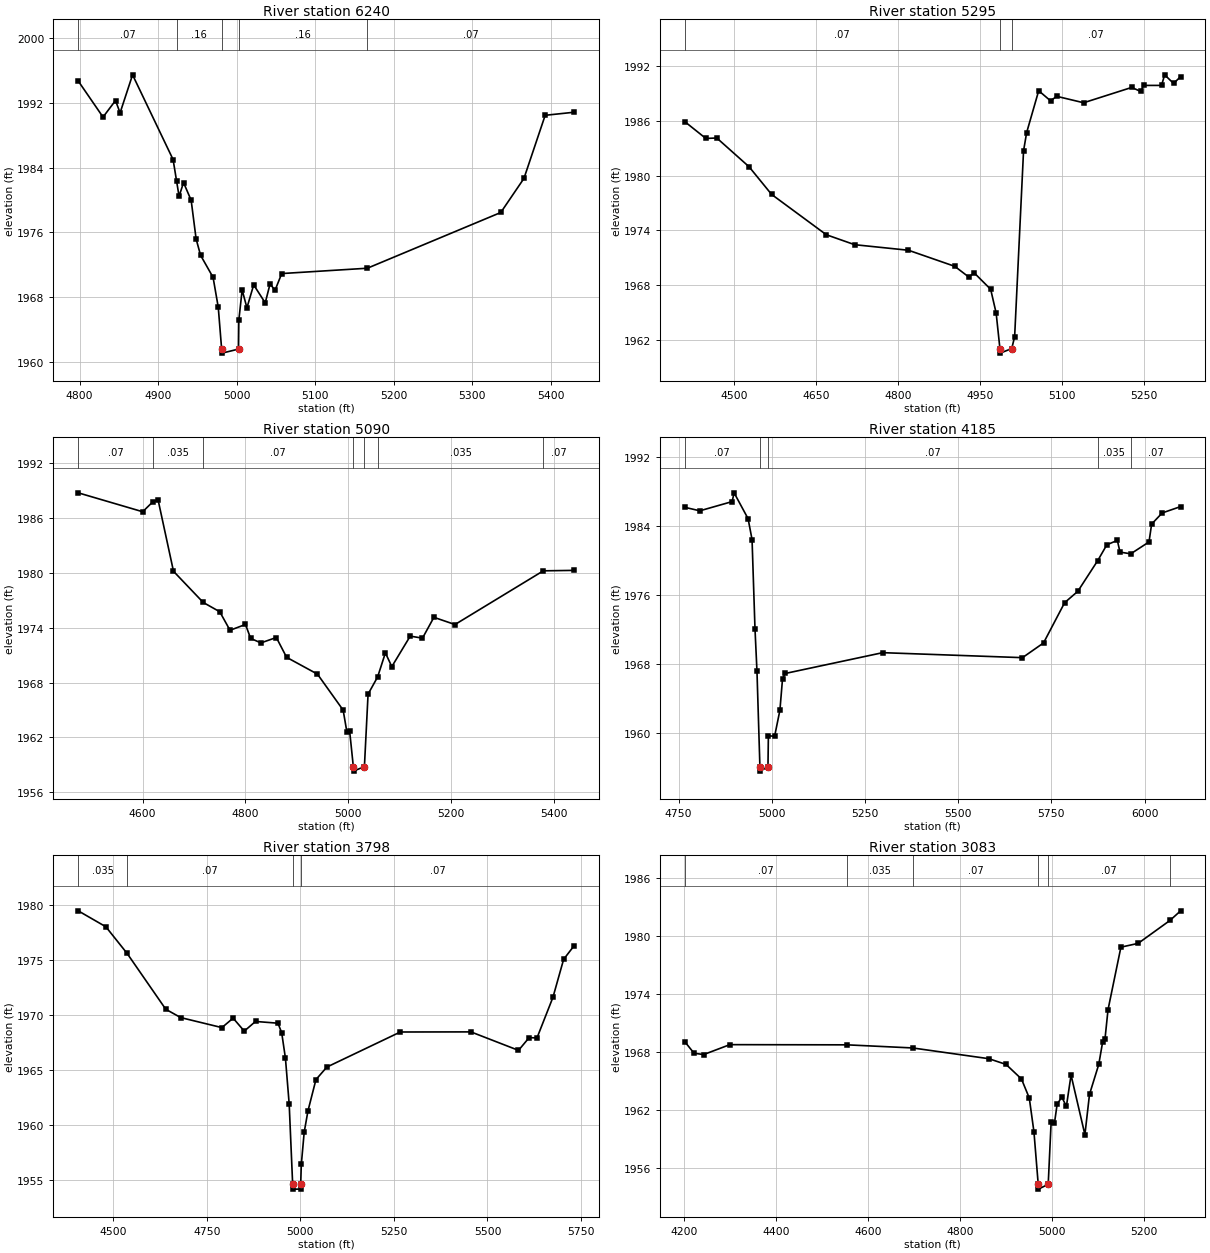
Type RM Length L Ch R = 1 ,6240    ,945,945,945
BEGIN DESCRIPTION:
Bluff Creek 4.0
END DESCRIPTION:
XS GIS Cut Line= 3
       1409980.2      6878937.07       1409804.6      6878837.83
        1409455.        6878588.
#Sta/Elev= 30
  4798.3 1994.73  4829.9 1990.26  4845.8 1992.31  4851.6 1990.78  4867.5 1995.49
  4919.1    1985  4923.6 1982.31  4926.7 1980.45  4932.4 1982.15  4942.1 1979.96
  4948.4 1975.17  4954.1 1973.15    4970 1970.42  4976.6 1966.72  4980.9 1961.54
  4981.4 1961.04  5002.4 1961.54  5002.8 1965.13    5007 1968.86  5013.1 1966.65
  5021.7 1969.49  5036.4 1967.26  5042.6 1969.63  5048.8  1968.8  5057.4 1970.89
  5166.4 1971.55  5336.3 1978.45  5365.8 1982.67  5392.8 1990.48  5429.7 1990.86
#Mann= 5 ,-1 , 0
  4798.3     .07       0  4923.6     .16       0  4980.9     .07       0
  5002.4     .16       0  5166.4     .07       0
Bank Sta=4980.9,5002.4
XS Rating Curve= 0 ,0
Exp/Cntr=0.3,0.1

Type RM Length L Ch R = 1 ,5295    ,205,205,205
BEGIN DESCRIPTION:
Bluff Creek 3.0
END DESCRIPTION:
XS GIS Cut Line= 3
      1409976.55      6878726.64      1409944.79       6878137.5
      1409795.97      6877857.83
#Sta/Elev= 30
    4410 1985.93  4448.7 1984.08  4468.7 1984.13  4527.7 1980.98  4568.9 1977.95
    4669 1973.53  4720.8 1972.44  4819.2 1971.83  4903.8 1970.07  4929.4  1968.9
  4939.4 1969.35  4969.5 1967.55  4979.5 1964.95  4986.4 1961.06  4986.9 1960.56
    5008 1961.06  5013.3 1962.35  5029.6 1982.72  5035.3 1984.73  5057.3 1989.31
  5079.2 1988.19  5089.9  1988.7  5139.5 1987.99  5227.4 1989.67  5243.7 1989.23
  5249.3 1989.89  5281.9 1989.89  5287.6 1991.05  5303.9 1990.11  5316.8 1990.85
#Mann= 3 ,-1 , 0
    4410     .07       0  4986.4     .07       0    5008     .07       0
Bank Sta=4986.4,5008
XS Rating Curve= 0 ,0
Exp/Cntr=0.3,0.1

Type RM Length L Ch R = 1 ,5090    ,905,905,905
BEGIN DESCRIPTION:
Bluff Creek 2.0
END DESCRIPTION:
XS GIS Cut Line= 3
      1410160.12      6878663.39      1410150.08      6878138.09
       1410042.1      6877711.96
#Sta/Elev= 30
  4474.6 1988.78    4600 1986.71  4619.7 1987.79    4630 1988.01    4660 1980.19
  4717.8 1976.78    4750 1975.76    4770 1973.73  4800.1 1974.37  4810.1 1972.84
  4830.1 1972.35  4860.1 1972.94  4880.1 1970.77  4940.1 1968.93  4990.1 1964.99
  4997.5 1962.56  5002.8 1962.67  5009.9 1958.81  5010.4 1958.31  5031.5 1958.81
  5038.6 1966.74  5057.2 1968.62  5072.3 1971.26  5084.8 1969.75  5120.6 1973.09
  5144.5 1972.87  5166.7 1975.15  5207.7 1974.36  5379.6 1980.24  5439.6 1980.29
#Mann= 7 ,-1 , 0
  4474.6     .07       0  4619.7    .035       0  4717.8     .07       0
  5009.9     .07       0  5031.5     .07       0  5057.2    .035       0
  5379.6     .07       0
Bank Sta=5009.9,5031.5
XS Rating Curve= 0 ,0
Exp/Cntr=0.3,0.1

Type RM Length L Ch R = 1 ,4185    ,387,387,387
BEGIN DESCRIPTION:
Bluff Creek 1.0
END DESCRIPTION:
XS GIS Cut Line= 3
      1410904.98      6878337.96      1410825.53      6878118.29
      1410055.01      6877338.01
#Sta/Elev= 30
  4766.4 1986.21    4807  1985.8  4893.6 1986.87    4899 1987.89  4936.5 1984.88
  4947.1 1982.46    4955 1972.07  4960.3 1967.15  4968.2 1956.04  4968.7 1955.54
  4989.8 1956.04  4990.9 1959.65  5007.6 1959.59  5021.8 1962.61  5028.8 1966.25
  5035.9 1966.89  5297.5 1969.31  5672.4 1968.73  5728.9 1970.44  5785.5 1975.12
  5820.8 1976.44  5874.4 1980.02  5898.7 1981.85  5926.9 1982.36    5934    1981
  5962.8  1980.8  6011.8 1982.18  6018.8 1984.25  6047.1 1985.55  6096.6 1986.29
#Mann= 5 ,-1 , 0
  4766.4     .07       0  4968.2     .07       0  4989.8     .07       0
  5874.4    .035       0  5962.8     .07       0
Bank Sta=4968.2,4989.8
XS Rating Curve= 0 ,0
Exp/Cntr=0.3,0.1

Type RM Length L Ch R = 1 ,3798    ,715,715,715
BEGIN DESCRIPTION:
Bluff Creek 4278
END DESCRIPTION:
XS GIS Cut Line= 5
      1411076.05       6878181.9      1411072.44      6877755.67
      1410905.21      6877758.05      1410595.01      6877799.07
       1410279.1      6877524.27
#Sta/Elev= 30
  4406.5  1979.5  4480.4 1978.05  4537.3 1975.62  4640.4 1970.55  4680.4 1969.79
  4790.4 1968.88  4820.4 1969.74  4850.2 1968.56  4880.2 1969.44  4940.2 1969.28
  4950.2 1968.41  4960.2 1966.09  4970.2 1961.93  4979.4 1954.69  4979.9 1954.19
  5000.5 1954.19    5001 1954.69  5002.6 1956.44  5010.3 1959.37  5020.4 1961.31
  5041.7 1964.15  5070.8 1965.29  5267.1 1968.48  5455.7 1968.49  5582.9 1966.81
  5611.4 1967.97  5632.3 1967.94    5675 1971.64  5703.5 1975.09  5731.6 1976.33
#Mann= 4 ,-1 , 0
  4406.5    .035       0  4537.3     .07       0  4979.4     .07       0
    5001     .07       0
Bank Sta=4979.4,5001
XS Rating Curve= 0 ,0
Exp/Cntr=0.3,0.1

Type RM Length L Ch R = 1 ,3083    ,382,382,382
BEGIN DESCRIPTION:
Bluff Creek 4277
END DESCRIPTION:
XS GIS Cut Line= 5
      1411115.13      6877736.61      1410815.63      6877421.49
      1410455.99       6877472.6      1410304.21      6877486.57
      1410204.37      6877408.43
#Sta/Elev= 30
    4202  1969.1  4222.4 1967.89  4243.4 1967.76  4300.1 1968.78  4554.8 1968.76
    4697 1968.44  4862.7 1967.33    4900 1966.74  4933.5 1965.24  4950.5 1963.27
  4960.6 1959.79  4969.9 1954.37  4970.4 1953.87  4991.6 1954.37    4998 1960.84
  5005.2 1960.69    5011 1962.63  5021.1 1963.37  5031.1 1962.41  5041.2 1965.64
  5071.3 1959.49  5081.3 1963.65  5101.4 1966.74    5110  1969.1    5115 1969.39
  5121.5 1972.38  5149.5 1978.84  5186.9 1979.23  5256.1  1981.6  5279.2 1982.59
#Mann= 6 ,-1 , 0
    4202     .07       0  4554.8    .035       0    4697     .07       0
  4969.9     .07       0  4991.6     .07       0  5256.1    .035       0
Bank Sta=4969.9,4991.6
XS Rating Curve= 0 ,0
Exp/Cntr=0.3,0.1

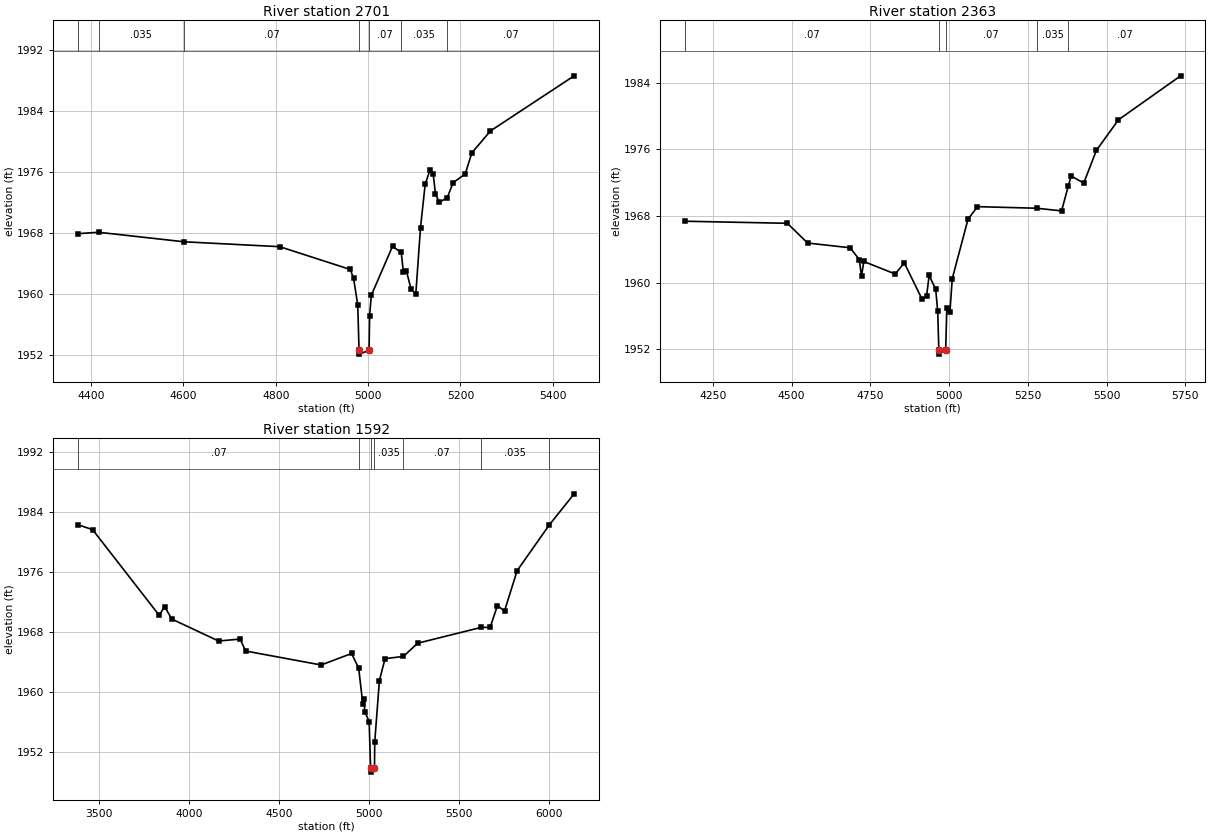
Type RM Length L Ch R = 1 ,2701    ,338,338,338
BEGIN DESCRIPTION:
Bluff Creek 4276
END DESCRIPTION:
XS GIS Cut Line= 3
      1410959.59      6877443.16      1410407.33      6877143.96
      1409965.64      6877078.58
#Sta/Elev= 30
  4371.9 1967.89  4416.1 1968.07  4601.6 1966.82  4808.4 1966.18  4961.4 1963.19
  4968.5 1962.05  4977.6 1958.53  4980.4 1952.58  4980.9 1952.08  5002.1 1952.58
  5003.3 1957.14    5007  1959.8  5052.9 1966.22  5071.8 1965.43  5076.5 1962.85
  5083.2 1962.94  5093.3 1960.58  5103.4 1959.98  5113.6 1968.69  5123.7 1974.38
  5133.8 1976.18    5141 1975.73    5146 1973.14    5154 1971.99  5171.5 1972.61
  5184.3 1974.57  5210.5 1975.73  5224.8 1978.49  5265.2 1981.37  5446.5  1988.6
#Mann= 7 ,-1 , 0
  4371.9     .07       0  4416.1    .035       0  4601.6     .07       0
  4980.4     .07       0  5002.1     .07       0  5071.8    .035       0
  5171.5     .07       0
Bank Sta=4980.4,5002.1
XS Rating Curve= 0 ,0
Exp/Cntr=0.3,0.1

Type RM Length L Ch R = 1 ,2363    ,771,771,771
BEGIN DESCRIPTION:
Bluff Creek 4274
END DESCRIPTION:
XS GIS Cut Line= 5
       1411133.2      6877629.77       1411024.7       6877273.9
        1410655.      6876987.98      1410647.09      6876813.83
      1410088.56      6876861.45
#Sta/Elev= 30
  4160.6 1967.38  4486.5 1967.13  4550.8 1964.76  4685.8 1964.19  4714.7 1962.78
  4721.9 1960.78  4729.2 1962.54  4828.8 1961.04  4857.8 1962.37  4913.9 1958.03
  4928.4 1958.34  4936.6 1960.86  4957.4 1959.21  4963.8 1956.55  4967.4 1951.91
  4967.9 1951.41  4989.1 1951.91  4992.7 1956.91  5002.5 1956.44    5010 1960.48
    5060 1967.62  5090.1 1969.13  5278.6 1968.94  5357.1 1968.62  5378.2 1971.61
  5387.2 1972.82  5427.3 1971.96  5467.5 1975.89  5537.7 1979.57  5734.9 1984.85
#Mann= 5 ,-1 , 0
  4160.6     .07       0  4967.4     .07       0  4989.1     .07       0
  5278.6    .035       0  5378.2     .07       0
Bank Sta=4967.4,4989.1
XS Rating Curve= 0 ,0
Exp/Cntr=0.3,0.1

Type RM Length L Ch R = 1 ,1592    ,0,0,0
BEGIN DESCRIPTION:
Bluff Creek 0.1
END DESCRIPTION:
XS GIS Cut Line= 5
        1411205.      6878388.02      1411243.08      6876868.85
      1411155.44      6876832.82      1410894.67      6876743.32
      1410028.24      6876765.09
#Sta/Elev= 30
  3385.6 1982.28  3465.6 1981.63  3835.8 1970.23  3865.8  1971.4  3905.8 1969.73
  4165.9 1966.81  4285.9 1967.07  4315.9 1965.48    4736 1963.62  4905.2 1965.15
  4944.5 1963.21  4967.9 1958.38  4973.3 1959.13  4978.9 1957.42  5002.9 1956.08
  5010.8 1949.86  5011.3 1949.36  5032.5 1949.86  5033.9 1953.37  5059.8 1961.55
  5091.1 1964.46  5193.2 1964.76  5272.9 1966.52  5625.3 1968.62  5675.5 1968.63
  5715.5  1971.5  5755.5 1970.82  5825.5 1976.18  6004.9 1982.28  6142.4  1986.4
#Mann= 7 ,-1 , 0
  3385.6     .07       0  4944.5    .035       0  5010.8    .035       0
  5032.5    .035       0  5193.2     .07       0  5625.3    .035       0
  6004.9     .07       0
Bank Sta=5010.8,5032.5
XS Rating Curve= 0 ,0
Exp/Cntr=0.3,0.1

Chan Stop Cuts=-1
Use User Specified Reach Order=0
Composite Channel Slope=5