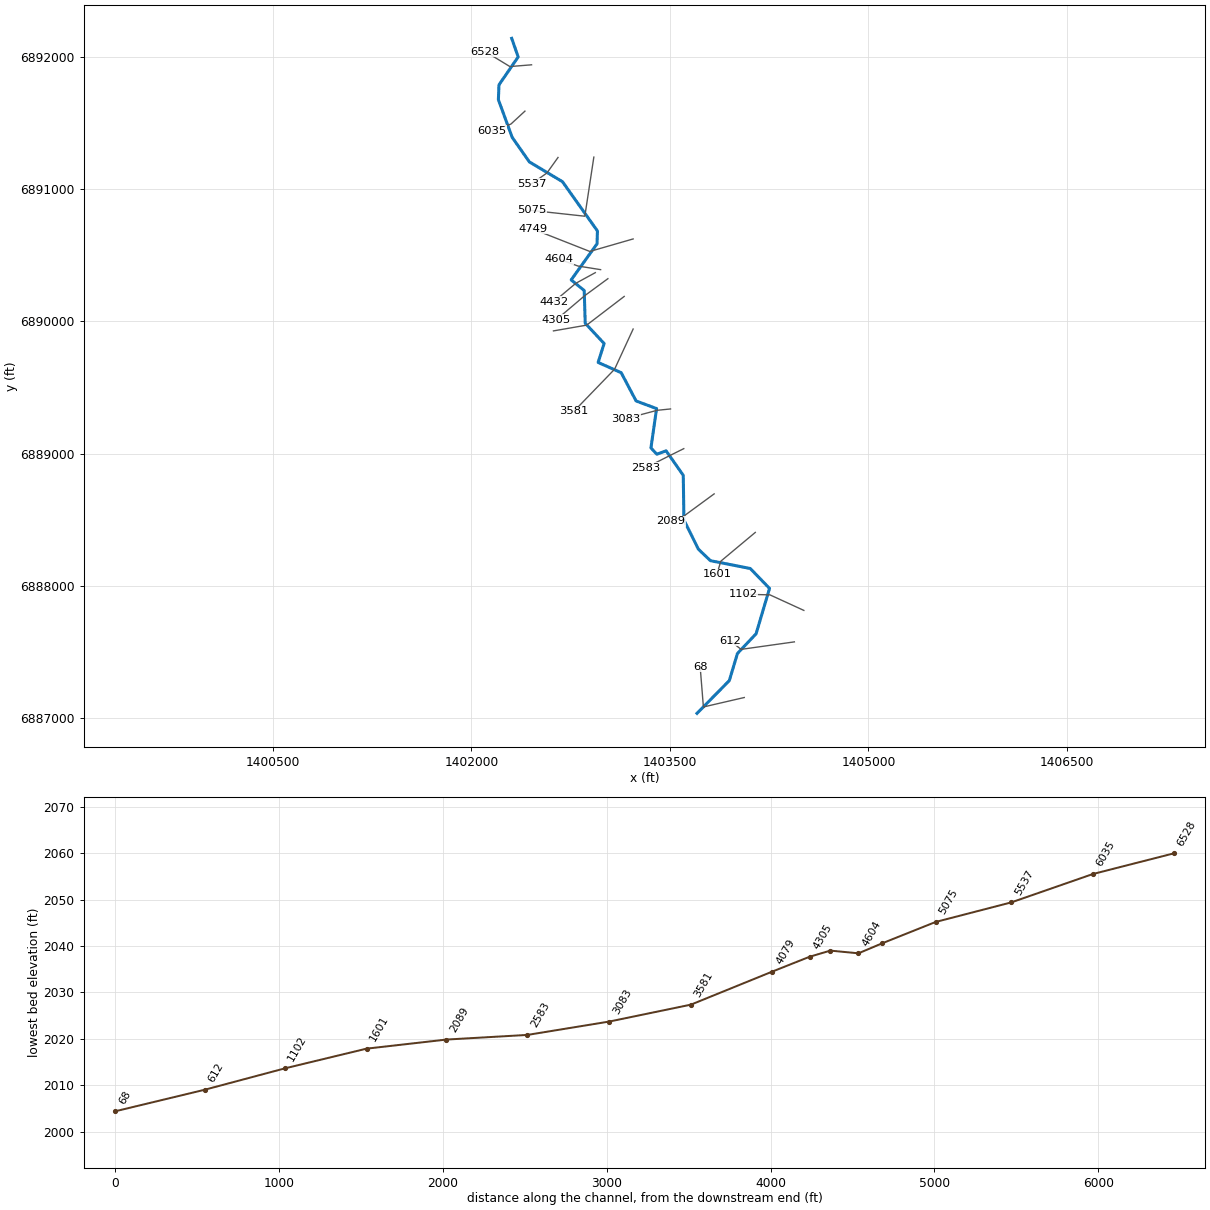
--- Bluff Creek Trib1.prj (project) ---

Proj Title=Bluff Creek Trib1 Base Level Engineering
Current Plan=p01
Default Exp/Contr=0.3,0.1
English Units
Geom File=g01
Flow File=f01
Plan File=p01
Y Axis Title=Elevation
X Axis Title(PF)=Main Channel Distance
X Axis Title(XS)=Station
BEGIN DESCRIPTION:
Bluff Creek Trib1
END DESCRIPTION:
DSS Export Rating Curves= 0
DSS Export Rating Curve Sorted= 0
DSS Export Volume Flow Curves= 0
DXF OffsetX= 0
DXF OffsetY= 0
DXF ScaleX= 1
DXF ScaleY= 10

--- Bluff Creek Trib1.p01 (plan) ---

Plan Title=Multiple Run
Short Identifier=Multiple
Geom File=g01
Flow File=f01
Subcritical Flow
K Sum by GR= 0
Std Step Tol= 0.01
Critical Tol= 0.01
Num of Std Step Trials= 20
Max Error Tol= 0.3
Flow Tol Ratio= 0.001
Split Flow NTrial= 30
Split Flow Tol= 0.02
Split Flow Ratio= 0.02
Log Output Level= 0
Friction Slope Method= 1
Unsteady Friction Slope Method= 2
Unsteady Bridges Friction Slope Method= 1
Parabolic Critical Depth
Global Vel Dist=  1 , 1 , 1
Global Log Level= 0
CheckData=True
Encroach Param= -1, 0, 0, 0
BEGIN DESCRIPTION:
Multiple Run
END DESCRIPTION:

--- Bluff Creek Trib1.f01 (steady flow) ---

Flow Title=Multiple
Number of Profiles=7
Profile Names=10-year,25-year,50-year,1pct_min,100-year,1pct_plu,500-year
River Rch & RM= Bluff Creek Trib,Reach-1,6528
     284     402     502     312     622    1241     967
River Rch & RM= Bluff Creek Trib,Reach-1,5075
     343     491     617     385     768    1533    1209
River Rch & RM= Bluff Creek Trib,Reach-1,3581
     505     739     942     596    1190    2375    1924
River Rch & RM= Bluff Creek Trib,Reach-1,2583
     546     800    1021     647    1291    2576    2091
Boundary for River Rch & Prof#=Bluff Creek Trib,Reach-1,1
Up Type=0
Dn Type=3
Dn Slope=0.005
Boundary for River Rch & Prof#=Bluff Creek Trib,Reach-1,2
Up Type=0
Dn Type=3
Dn Slope=0.005
Boundary for River Rch & Prof#=Bluff Creek Trib,Reach-1,3
Up Type=0
Dn Type=3
Dn Slope=0.005
Boundary for River Rch & Prof#=Bluff Creek Trib,Reach-1,4
Up Type=0
Dn Type=3
Dn Slope=0.005
Boundary for River Rch & Prof#=Bluff Creek Trib,Reach-1,5
Up Type=0
Dn Type=3
Dn Slope=0.005
Boundary for River Rch & Prof#=Bluff Creek Trib,Reach-1,6
Up Type=0
Dn Type=3
Dn Slope=0.005
Boundary for River Rch & Prof#=Bluff Creek Trib,Reach-1,7
Up Type=0
Dn Type=3
Dn Slope=0.005

--- Bluff Creek Trib1.g01 (geometry) ---

Geom Title=Existing Conditions

River Reach=Bluff Creek Trib,Reach-1
Reach XY= 30
      1402305.00      6892138.00      1402353.92      6891997.62
      1402208.74      6891786.44      1402204.51      6891674.20
      1402308.83      6891389.58      1402438.29      6891204.64
      1402688.50      6891055.05      1402952.92      6890682.51
      1402949.60      6890585.57      1402754.47      6890312.88
      1402852.88      6890232.73      1402860.46      6889985.55
      1403003.26      6889832.37      1402958.03      6889689.39
      1403132.19      6889611.95      1403244.90      6889398.39
      1403399.72      6889340.71      1403357.05      6889043.46
      1403401.38      6888995.88      1403471.70      6889021.62
      1403601.25      6888836.45      1403606.20      6888498.50
      1403715.75      6888278.29      1403806.48      6888191.61
      1404107.45      6888132.53      1404253.04      6887982.11
      1404151.39      6887639.50      1404010.52      6887490.43
      1403949.17      6887285.70      1403705.00      6887038.00

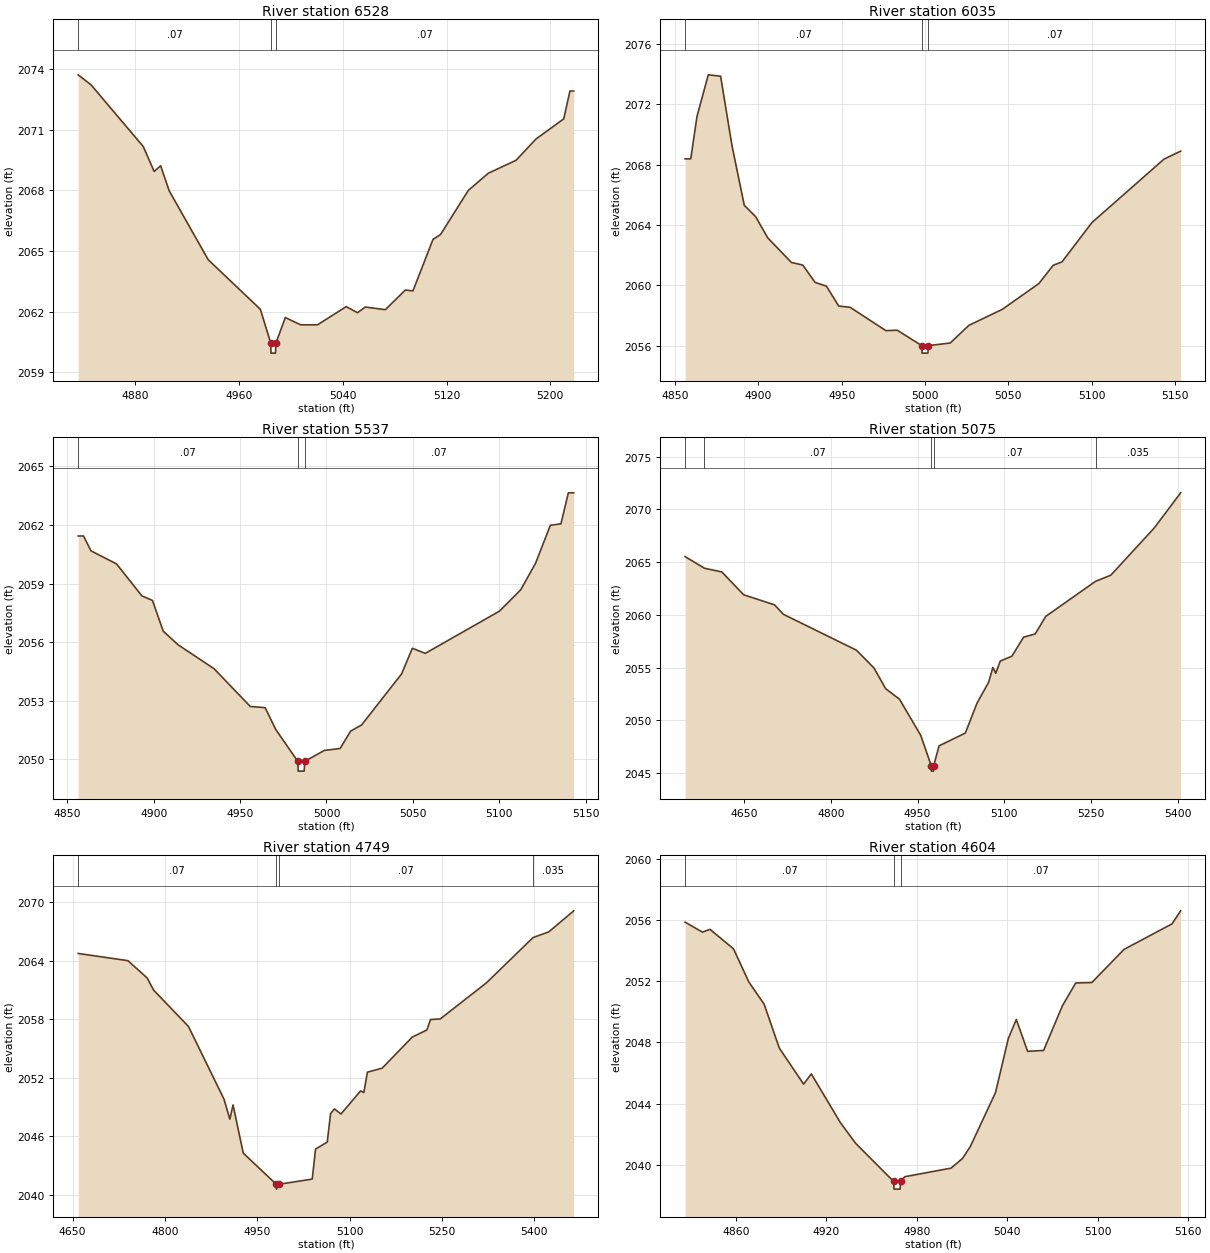
Type RM Length L Ch R = 1,6528,493,493,493
BEGIN DESCRIPTION:
Bluff Creek Trib1 12.0
END DESCRIPTION:
XS GIS Cut Line= 3
      1402455.00      6891938.00      1402291.44      6891924.76
      1402105.03      6892037.98
#Sta/Elev= 30
  4835.9 2073.72  4845.9 2073.22  4886.1 2070.17  4894.5 2068.94  4899.5 2069.22
  4906.1 2067.98  4936.2 2064.57  4976.4 2062.12  4984.4 2060.45  4984.6 2059.95
  4988.1 2059.95  4988.4 2060.45  4995.7 2061.71  5007.5 2061.35  5020.5 2061.35
  5042.6 2062.25  5051.4 2061.95  5057.3 2062.23  5072.8 2062.10  5088.2 2063.07
  5094.1 2063.03  5109.6 2065.58  5115.4 2065.82  5136.8 2068.00  5152.2 2068.85
  5173.6 2069.49  5189.1 2070.55  5210.4 2071.54  5215.2 2072.92  5218.1 2072.92
#Mann=3,-1,0
  4835.9    0.07       0  4984.4    0.07       0  4988.4    0.07       0
Bank Sta=4984.4,4988.4
Exp/Cntr=0.3,0.1

Type RM Length L Ch R = 1,6035,498,498,498
BEGIN DESCRIPTION:
Bluff Creek Trib1 11.0
END DESCRIPTION:
XS GIS Cut Line= 3
      1402405.02      6891588.02      1402299.23      6891490.32
      1402155.03      6891438.01
#Sta/Elev= 30
  4856.0 2068.39  4859.4 2068.39  4863.1 2071.19  4869.9 2073.96  4877.3 2073.87
  4884.1 2069.28  4891.5 2065.31  4898.3 2064.56  4905.6 2063.15  4919.8 2061.52
  4926.6 2061.35  4934.0 2060.20  4940.8 2059.95  4948.2 2058.63  4955.0 2058.55
  4976.5 2057.00  4983.3 2057.03  4998.0 2056.01  4998.2 2055.51  5001.7 2055.51
  5002.0 2056.01  5015.1 2056.18  5026.3 2057.35  5046.3 2058.41  5068.3 2060.12
  5076.9 2061.33  5082.2 2061.56  5100.2 2064.17  5143.4 2068.37  5153.4 2068.90
#Mann=3,-1,0
  4856.0    0.07       0  4998.0    0.07       0  5002.0    0.07       0
Bank Sta=4998,5002
Exp/Cntr=0.3,0.1

Type RM Length L Ch R = 1,5537,462,462,462
BEGIN DESCRIPTION:
Bluff Creek Trib1 10.0
END DESCRIPTION:
XS GIS Cut Line= 3
      1402655.02      6891238.02      1402571.55      6891121.05
      1402455.01      6891038.01
#Sta/Elev= 30
  4856.3 2061.44  4859.4 2061.44  4863.7 2060.68  4878.5 2060.01  4893.2 2058.37
  4899.3 2058.14  4905.5 2056.57  4914.1 2055.87  4935.0 2054.64  4955.9 2052.71
  4964.5 2052.65  4970.6 2051.54  4983.4 2049.90  4983.6 2049.40  4987.1 2049.40
  4987.4 2049.90  4998.8 2050.46  5007.9 2050.56  5014.0 2051.45  5020.3 2051.76
  5043.5 2054.38  5049.7 2055.69  5057.2 2055.43  5100.1 2057.59  5112.4 2058.68
  5121.0 2060.04  5129.6 2061.99  5135.7 2062.06  5140.0 2063.65  5143.1 2063.65
#Mann=3,-1,0
  4856.3    0.07       0  4983.4    0.07       0  4987.4    0.07       0
Bank Sta=4983.4,4987.4
Exp/Cntr=0.3,0.1

Type RM Length L Ch R = 1,5075,326,326,326
BEGIN DESCRIPTION:
Bluff Creek Trib1 9.0
END DESCRIPTION:
XS GIS Cut Line= 3
      1402925.65      6891240.69      1402857.54      6890794.05
      1402455.04      6890838.00
#Sta/Elev= 30
  4548.2 2065.52  4581.6 2064.42  4611.6 2064.07  4649.5 2061.90  4702.7 2060.95
  4718.1 2060.05  4844.3 2056.65  4874.6 2054.97  4894.9 2053.00  4918.8 2052.00
  4955.5 2048.58  4973.8 2045.68  4974.0 2045.18  4977.5 2045.18  4977.8 2045.68
  4987.3 2047.58  5032.7 2048.79  5052.9 2051.63  5073.0 2053.61  5080.2 2055.01
  5085.2 2054.46  5093.1 2055.62  5113.2 2056.08  5133.3 2057.88  5153.5 2058.19
  5171.6 2059.85  5257.8 2063.18  5284.2 2063.76  5359.3 2068.24  5404.9 2071.57
#Mann=5,-1,0
  4548.2   0.035       0  4581.6    0.07       0  4973.8    0.07       0
  4977.8    0.07       0  5257.8   0.035       0
Bank Sta=4973.8,4977.8
Exp/Cntr=0.3,0.1

Type RM Length L Ch R = 1,4749,145,145,145
BEGIN DESCRIPTION:
Bluff Creek Trib1 8.1
END DESCRIPTION:
XS GIS Cut Line= 3
      1403222.76      6890622.49      1402895.13      6890527.95
      1402463.03      6890698.12
#Sta/Elev= 30
  4659.0 2064.75  4739.9 2064.01  4771.2 2062.23  4781.6 2060.99  4838.2 2057.27
  4896.1 2049.80  4905.5 2047.76  4910.7 2049.22  4927.3 2044.28  4980.9 2041.09
  4981.2 2040.59  4985.5 2041.09  5039.4 2041.62  5044.8 2044.70  5063.8 2045.41
  5069.2 2048.32  5075.4 2048.82  5086.1 2048.29  5118.0 2050.66  5123.3 2050.50
  5129.1 2052.58  5153.1 2052.99  5201.9 2056.17  5225.8 2056.91  5231.7 2057.98
  5247.3 2058.03  5322.6 2061.74  5398.3 2066.38  5423.9 2066.96  5464.4 2069.12
#Mann=4,-1,0
  4659.0    0.07       0  4980.9    0.07       0  4985.5    0.07       0
  5398.3   0.035       0
Bank Sta=4980.9,4985.5
Exp/Cntr=0.3,0.1

Type RM Length L Ch R = 1,4604,172,172,172
BEGIN DESCRIPTION:
Bluff Creek Trib1 8.0
END DESCRIPTION:
XS GIS Cut Line= 3
      1402976.73      6890390.45      1402805.30      6890417.86
      1402659.65      6890471.16
#Sta/Elev= 30
  4826.4 2055.85  4837.9 2055.20  4842.9 2055.38  4858.5 2054.11  4868.7 2051.94
  4878.8 2050.50  4888.9 2047.63  4905.0 2045.28  4910.1 2045.95  4929.4 2042.77
  4939.5 2041.42  4964.7 2038.93  4965.0 2038.43  4969.0 2038.43  4969.3 2038.93
  4972.1 2039.24  5002.8 2039.80  5010.3 2040.42  5015.6 2041.21  5032.3 2044.73
  5040.8 2048.26  5046.1 2049.50  5053.6 2047.42  5064.2 2047.48  5076.7 2050.40
  5085.5 2051.88  5096.2 2051.91  5117.5 2054.07  5149.4 2055.74  5155.1 2056.59
#Mann=3,-1,0
  4826.4    0.07       0  4964.7    0.07       0  4969.3    0.07       0
Bank Sta=4964.7,4969.3
Exp/Cntr=0.3,0.1

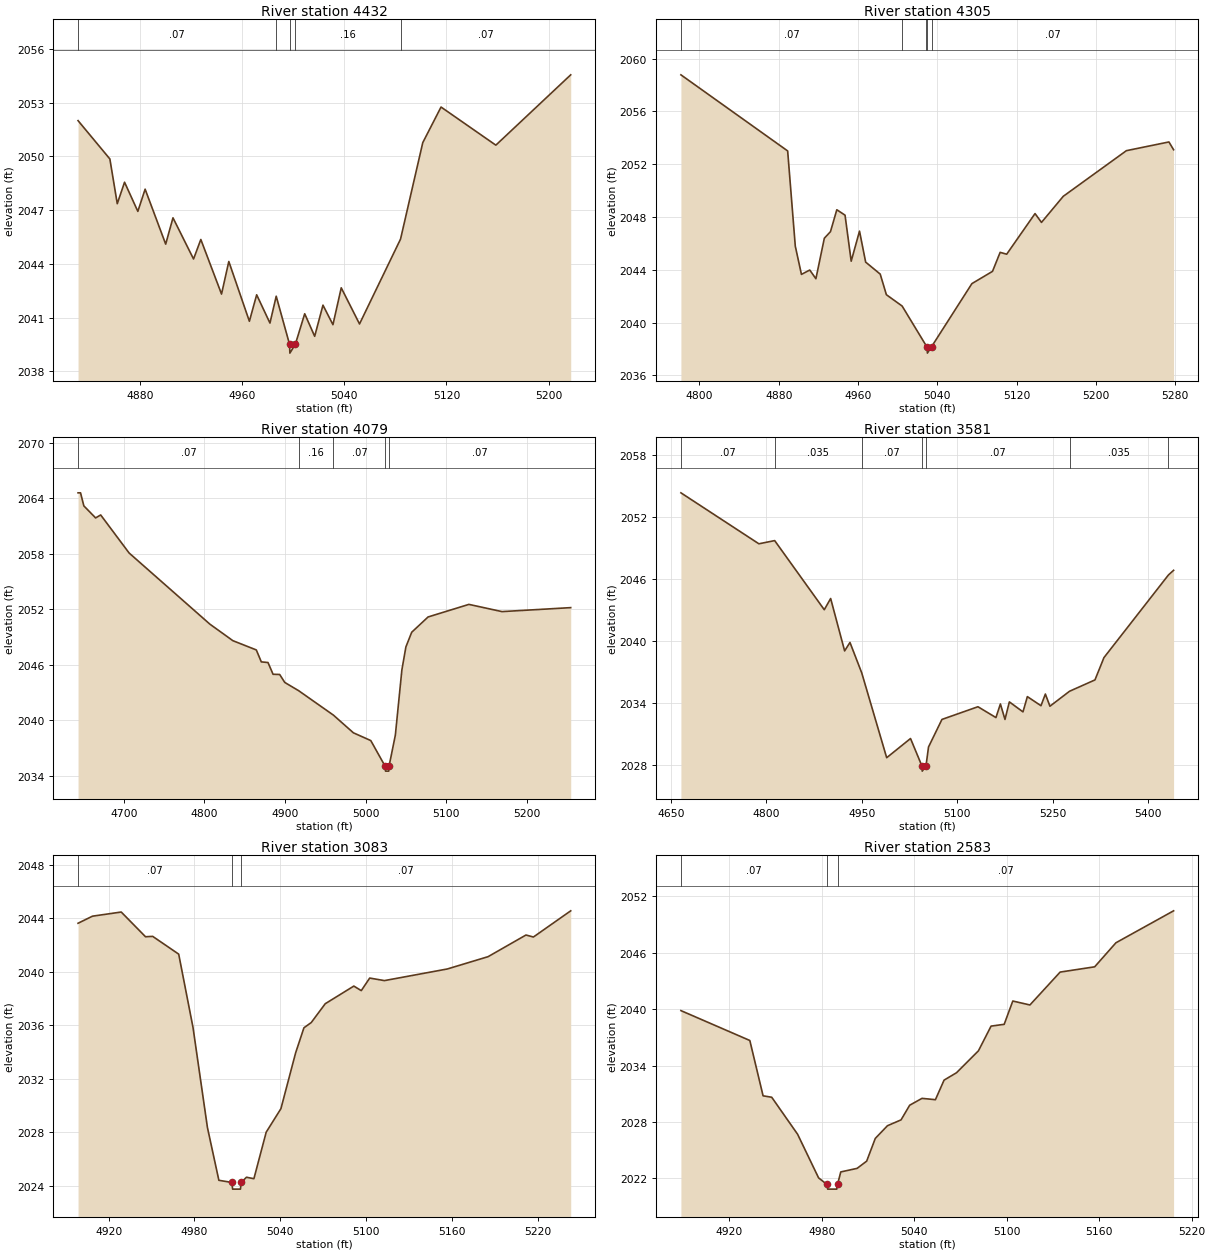
Type RM Length L Ch R = 1,4432,127,127,127
BEGIN DESCRIPTION:
Bluff Creek Trib1 7.2
END DESCRIPTION:
XS GIS Cut Line= 3
      1402936.82      6890367.78      1402789.15      6890287.04
      1402622.76      6890147.27
#Sta/Elev= 30
  4831.7 2052.00  4856.6 2049.86  4862.4 2047.36  4868.1 2048.56  4878.5 2046.93
  4884.2 2048.17  4900.3 2045.10  4906.0 2046.57  4922.1 2044.27  4927.8 2045.36
  4944.0 2042.31  4949.7 2044.13  4965.8 2040.79  4971.5 2042.27  4981.9 2040.69
  4986.8 2042.19  4997.2 2039.51  4997.5 2039.01  5001.8 2039.51  5009.1 2041.21
  5016.9 2039.95  5023.4 2041.69  5031.2 2040.60  5037.7 2042.66  5052.0 2040.64
  5084.1 2045.38  5101.5 2050.77  5115.8 2052.76  5158.7 2050.63  5217.3 2054.56
#Mann=5,-1,0
  4831.7    0.07       0  4986.8    0.16       0  4997.2    0.07       0
  5001.8    0.16       0  5084.1    0.07       0
Bank Sta=4997.2,5001.8
Exp/Cntr=0.3,0.1

Type RM Length L Ch R = 1,4305,226,226,226
BEGIN DESCRIPTION:
Bluff Creek Trib1 7.1
END DESCRIPTION:
XS GIS Cut Line= 3
      1403031.80      6890322.17      1402855.49      6890192.78
      1402643.12      6890012.76
#Sta/Elev= 30
  4781.3 2058.78  4889.0 2053.01  4896.7 2045.79  4902.9 2043.65  4911.3 2043.98
  4917.5 2043.32  4926.0 2046.39  4932.2 2046.89  4938.6 2048.55  4946.9 2048.14
  4953.1 2044.65  4961.5 2046.93  4967.7 2044.58  4982.4 2043.67  4988.6 2042.11
  5004.5 2041.25  5028.3 2038.30  5029.7 2038.18  5030.0 2037.68  5034.3 2038.18
  5074.9 2042.95  5095.7 2043.88  5103.4 2045.32  5110.0 2045.18  5138.6 2048.26
  5145.1 2047.59  5167.1 2049.57  5230.8 2053.03  5273.7 2053.69  5278.4 2053.10
#Mann=5,-1,0
  4781.3    0.07       0  5004.5    0.16       0  5028.3    0.07       0
  5029.7    0.07       0  5034.3    0.07       0
Bank Sta=5029.7,5034.3
Exp/Cntr=0.3,0.1

Type RM Length L Ch R = 1,4079,498,498,498
BEGIN DESCRIPTION:
Bluff Creek Trib1 7.0
END DESCRIPTION:
XS GIS Cut Line= 3
      1403154.98      6890187.98      1402871.43      6889971.24
      1402620.49      6889927.62
#Sta/Elev= 30
  4643.1 2064.57  4646.2 2064.57  4650.3 2063.16  4664.9 2061.86  4671.2 2062.18
  4706.5 2058.07  4806.7 2050.39  4835.3 2048.60  4864.4 2047.60  4870.6 2046.31
  4878.9 2046.24  4885.2 2044.97  4893.4 2044.95  4899.7 2044.09  4917.1 2043.19
  4960.1 2040.56  4984.9 2038.65  5006.5 2037.81  5024.5 2035.01  5024.8 2034.51
  5028.8 2034.51  5029.1 2035.01  5037.0 2038.40  5045.1 2045.44  5050.1 2047.93
  5057.3 2049.51  5077.6 2051.16  5128.3 2052.52  5169.4 2051.74  5254.7 2052.17
#Mann=5,-1,0
  4643.1    0.07       0  4917.1    0.16       0  4960.1    0.07       0
  5024.5    0.07       0  5029.1    0.07       0
Bank Sta=5024.5,5029.1
Exp/Cntr=0.3,0.1

Type RM Length L Ch R = 1,3581,498,498,498
BEGIN DESCRIPTION:
Bluff Creek Trib1 6.0
END DESCRIPTION:
XS GIS Cut Line= 3
      1403222.57      6889941.73      1403082.36      6889638.04
      1402776.41      6889321.68
#Sta/Elev= 30
  4665.5 2054.34  4788.1 2049.40  4812.9 2049.71  4890.9 2043.01  4900.9 2044.10
  4922.9 2039.02  4931.3 2039.84  4949.8 2036.89  4989.0 2028.67  5026.5 2030.53
  5044.4 2027.87  5044.9 2027.37  5050.8 2027.87  5054.8 2029.71  5075.9 2032.38
  5132.5 2033.61  5160.8 2032.56  5167.8 2033.88  5175.0 2032.38  5181.9 2034.08
  5203.3 2033.11  5210.2 2034.59  5231.6 2033.71  5238.5 2034.84  5245.7 2033.66
  5276.5 2035.11  5316.5 2036.21  5330.6 2038.37  5432.0 2046.38  5440.1 2046.83
#Mann=7,-1,0
  4665.5    0.07       0  4812.9   0.035       0  4949.8    0.07       0
  5044.4    0.07       0  5050.8    0.07       0  5276.5   0.035       0
  5432.0    0.07       0
Bank Sta=5044.4,5050.8
Exp/Cntr=0.3,0.1

Type RM Length L Ch R = 1,3083,500,500,500
BEGIN DESCRIPTION:
Bluff Creek Trib1 5.0
END DESCRIPTION:
XS GIS Cut Line= 4
      1403505.01      6889338.00      1403404.14      6889327.69
      1403255.00      6889288.00      1403169.12      6889265.15
#Sta/Elev= 30
  4898.6 2043.62  4908.7 2044.15  4928.8 2044.46  4945.8 2042.61  4950.8 2042.64
  4969.0 2041.31  4979.0 2035.83  4989.1 2028.34  4997.1 2024.39  5006.2 2024.23
  5006.7 2023.73  5012.2 2023.73  5012.7 2024.23  5016.4 2024.62  5021.6 2024.51
  5030.2 2027.99  5040.5 2029.75  5050.8 2033.93  5056.6 2035.80  5061.7 2036.19
  5071.5 2037.60  5091.5 2038.92  5096.7 2038.58  5102.6 2039.52  5112.9 2039.33
  5156.9 2040.20  5185.4 2041.12  5211.9 2042.74  5217.1 2042.59  5243.2 2044.55
#Mann=3,-1,0
  4898.6    0.07       0  5006.2    0.07       0  5012.7    0.07       0
Bank Sta=5006.2,5012.7
Exp/Cntr=0.3,0.1

Type RM Length L Ch R = 1,2583,494,494,494
BEGIN DESCRIPTION:
Bluff Creek Trib1 4.0
END DESCRIPTION:
XS GIS Cut Line= 4
      1403605.03      6889038.02      1403505.21      6888988.56
      1403405.00      6888938.00      1403319.33      6888894.78
#Sta/Elev= 30
  4888.6 2039.85  4933.3 2036.67  4941.9 2030.78  4947.5 2030.63  4964.3 2026.69
  4977.9 2022.05  4983.3 2021.35  4983.8 2020.85  4989.7 2020.85  4990.2 2021.35
  4992.3 2022.68  5002.9 2023.06  5009.1 2023.83  5014.7 2026.25  5022.6 2027.60
  5031.4 2028.22  5037.0 2029.78  5045.0 2030.51  5053.7 2030.37  5059.3 2032.45
  5067.4 2033.24  5081.6 2035.57  5089.8 2038.20  5098.3 2038.39  5103.9 2040.87
  5115.0 2040.45  5134.6 2043.95  5157.0 2044.51  5170.8 2047.07  5208.2 2050.47
#Mann=3,-1,0
  4888.6    0.07       0  4983.3    0.07       0  4990.2    0.07       0
Bank Sta=4983.3,4990.2
Exp/Cntr=0.3,0.1

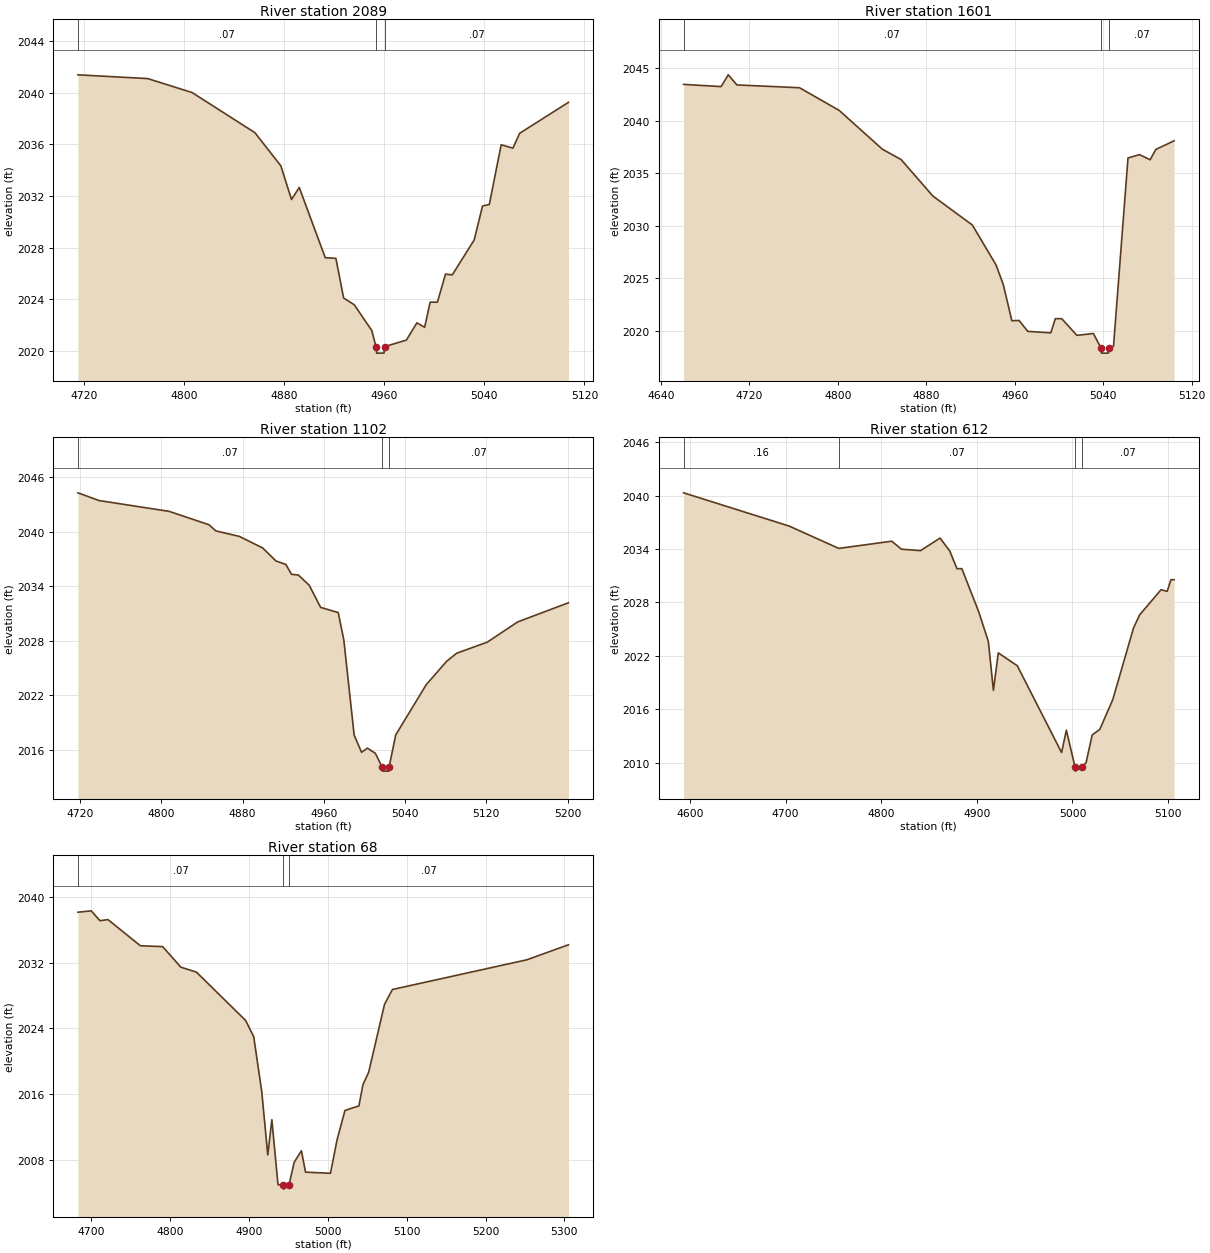
Type RM Length L Ch R = 1,2089,488,488,488
BEGIN DESCRIPTION:
Bluff Creek Trib1 3.0
END DESCRIPTION:
XS GIS Cut Line= 4
      1403834.56      6888696.27      1403755.00      6888638.00
      1403604.54      6888527.81      1403505.01      6888488.00
#Sta/Elev= 30
  4714.9 2041.37  4770.7 2041.08  4806.2 2040.00  4856.4 2036.90  4877.2 2034.33
  4885.7 2031.73  4891.9 2032.66  4912.7 2027.23  4921.2 2027.18  4927.4 2024.11
  4935.9 2023.59  4949.9 2021.60  4953.3 2020.35  4953.8 2019.85  4959.7 2019.85
  4960.2 2020.35  4977.6 2020.86  4986.0 2022.19  4992.2 2021.85  4996.6 2023.79
  5002.4 2023.79  5008.9 2025.96  5014.3 2025.90  5031.8 2028.60  5038.5 2031.23
  5043.9 2031.34  5053.4 2035.96  5062.8 2035.70  5068.2 2036.85  5107.2 2039.24
#Mann=3,-1,0
  4714.9    0.07       0  4953.3    0.07       0  4960.2    0.07       0
Bank Sta=4953.3,4960.2
Exp/Cntr=0.3,0.1

Type RM Length L Ch R = 1,1601,499,499,499
BEGIN DESCRIPTION:
Bluff Creek Trib1 2.0
END DESCRIPTION:
XS GIS Cut Line= 4
      1404145.46      6888405.24      1404005.00      6888288.00
      1403884.90      6888187.75      1403855.01      6888088.03
#Sta/Elev= 30
  4660.6 2043.47  4694.5 2043.26  4701.0 2044.38  4708.8 2043.42  4765.4 2043.15
  4801.3 2040.99  4840.3 2037.30  4857.2 2036.32  4885.9 2032.85  4921.7 2030.08
  4943.1 2026.28  4949.6 2024.43  4957.4 2020.97  4963.9 2021.00  4971.8 2019.96
  4992.6 2019.82  4996.7 2021.17  5002.5 2021.17  5016.2 2019.58  5031.1 2019.76
  5037.9 2018.39  5038.4 2017.89  5044.6 2017.89  5045.1 2018.39  5049.3 2018.55
  5062.4 2036.47  5072.8 2036.78  5082.4 2036.30  5087.6 2037.28  5104.1 2038.10
#Mann=3,-1,0
  4660.6    0.07       0  5037.9    0.07       0  5045.1    0.07       0
Bank Sta=5037.9,5045.1
Exp/Cntr=0.3,0.1

Type RM Length L Ch R = 1,1102,490,490,490
BEGIN DESCRIPTION:
Bluff Creek Trib1 1.0
END DESCRIPTION:
XS GIS Cut Line= 4
      1404512.30      6887815.93      1404355.00      6887888.00
      1404255.84      6887933.44      1404054.99      6887938.00
#Sta/Elev= 30
  4717.9 2044.27  4738.7 2043.42  4807.7 2042.23  4846.9 2040.76  4853.7 2040.08
  4876.7 2039.48  4899.7 2038.21  4912.9 2036.77  4922.7 2036.38  4928.2 2035.30
  4934.9 2035.23  4945.7 2034.09  4956.9 2031.66  4974.2 2031.09  4979.7 2028.09
  4989.9 2017.60  4997.2 2015.71  5002.9 2016.17  5010.8 2015.60  5017.2 2014.14
  5017.7 2013.64  5023.9 2013.64  5024.4 2014.14  5030.8 2017.62  5060.9 2023.16
  5080.9 2025.72  5090.9 2026.62  5120.9 2027.83  5150.9 2030.06  5200.9 2032.17
#Mann=3,-1,0
  4717.9    0.07       0  5017.2    0.07       0  5024.4    0.07       0
Bank Sta=5017.2,5024.4
Exp/Cntr=0.3,0.1

Type RM Length L Ch R = 1,612,544,544,544
BEGIN DESCRIPTION:
Bluff Creek Trib1 0.1
END DESCRIPTION:
XS GIS Cut Line= 4
      1404440.61      6887578.19      1404155.00      6887538.00
      1404037.88      6887521.52      1403954.96      6887588.03
#Sta/Elev= 30
  4593.3 2040.33  4703.7 2036.59  4755.6 2034.08  4811.0 2034.89  4821.1 2033.99
  4841.1 2033.83  4861.5 2035.24  4871.6 2033.80  4879.2 2031.80  4884.3 2031.80
  4901.9 2026.96  4912.0 2023.62  4917.3 2018.12  4922.4 2022.33  4942.3 2020.88
  4988.6 2011.12  4993.6 2013.63  5002.6 2009.53  5003.1 2009.03  5009.9 2009.53
  5014.2 2009.97  5020.6 2013.10  5028.6 2013.73  5042.2 2017.09  5063.8 2025.12
  5070.2 2026.60  5092.6 2029.43  5099.0 2029.25  5103.0 2030.56  5106.3 2030.56
#Mann=4,-1,0
  4593.3    0.16       0  4755.6    0.07       0  5002.6    0.07       0
  5009.9    0.07       0
Bank Sta=5002.6,5009.9
Exp/Cntr=0.3,0.1

Type RM Length L Ch R = 1,68,0,0,0
BEGIN DESCRIPTION:
Bluff Creek Trib1 4315
END DESCRIPTION:
XS GIS Cut Line= 3
      1404062.14      6887157.81      1403753.39      6887086.38
      1403728.83      6887390.49
#Sta/Elev= 30
  4683.1 2038.17  4700.0 2038.34  4711.0 2037.14  4721.2 2037.27  4762.3 2034.08
  4790.5 2033.98  4813.6 2031.47  4833.3 2030.87  4895.7 2024.98  4906.0 2023.00
  4916.2 2016.30  4923.8 2008.58  4929.0 2012.88  4936.8 2004.96  4943.4 2004.91
  4943.9 2004.41  4950.7 2004.91  4957.3 2007.68  4966.5 2009.09  4971.7 2006.48
  5003.3 2006.34  5011.7 2010.42  5021.7 2014.00  5039.4 2014.56  5044.5 2017.14
  5051.8 2018.67  5071.9 2026.95  5081.9 2028.75  5252.4 2032.37  5305.1 2034.20
#Mann=3,-1,0
  4683.1    0.07       0  4943.4    0.07       0  4950.7    0.07       0
Bank Sta=4943.4,4950.7
Exp/Cntr=0.3,0.1

Chan Stop Cuts=-1