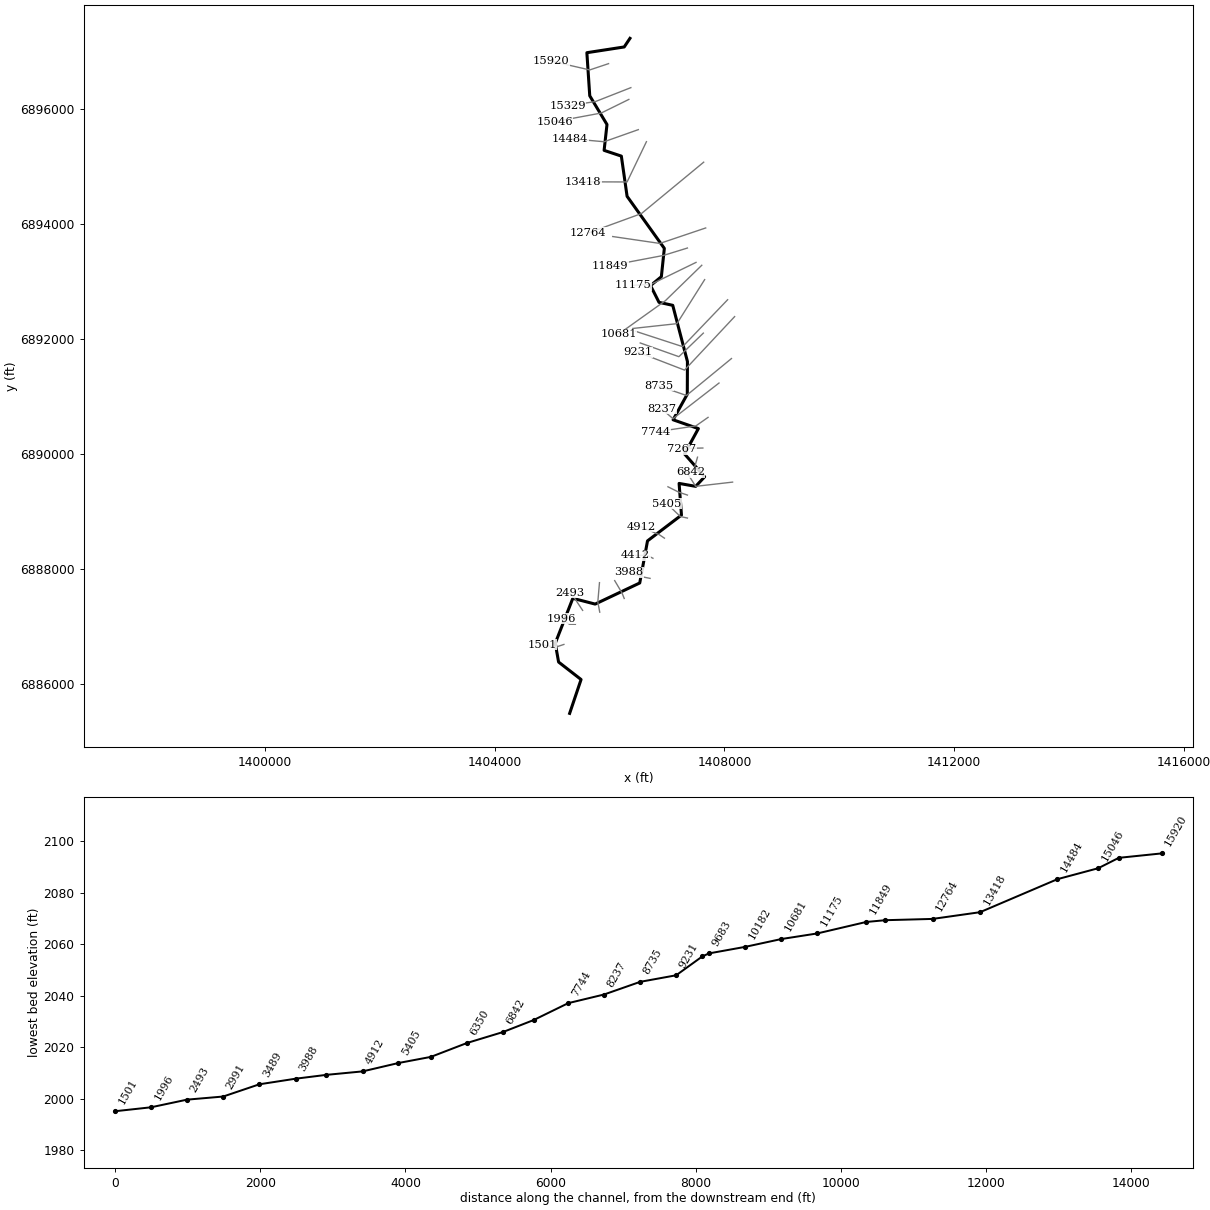
--- Bluff Creek Trib2.prj (project) ---

Proj Title=Bluff Creek Trib2 Base Level Engineering
Current Plan=p01
Default Exp/Contr=0.3,0.1
English Units
Geom File=g01
Flow File=f01
Plan File=p01
Y Axis Title=Elevation
X Axis Title(PF)=Main Channel Distance
X Axis Title(XS)=Station
BEGIN DESCRIPTION:
Bluff Creek Trib2
END DESCRIPTION:
DSS Export Rating Curves= 0
DSS Export Rating Curve Sorted= 0
DSS Export Volume Flow Curves= 0
DXF OffsetX= 0
DXF OffsetY= 0
DXF ScaleX= 1
DXF ScaleY= 10

--- Bluff Creek Trib2.p01 (plan) ---

Plan Title=Multiple Run
Short Identifier=Multiple
Geom File=g01
Flow File=f01
Subcritical Flow
K Sum by GR= 0
Std Step Tol= 0.01
Critical Tol= 0.01
Num of Std Step Trials= 20
Max Error Tol= 0.3
Flow Tol Ratio= 0.001
Split Flow NTrial= 30
Split Flow Tol= 0.02
Split Flow Ratio= 0.02
Log Output Level= 0
Friction Slope Method= 1
Unsteady Friction Slope Method= 2
Unsteady Bridges Friction Slope Method= 1
Parabolic Critical Depth
Global Vel Dist=  1 , 1 , 1
Global Log Level= 0
CheckData=True
Encroach Param= -1, 0, 0, 0
BEGIN DESCRIPTION:
Multiple Run
END DESCRIPTION:

--- Bluff Creek Trib2.f01 (steady flow) ---

Flow Title=Multiple
Number of Profiles=7
Profile Names=10-year,25-year,50-year,1pct_min,100-year,1pct_plu,500-year
River Rch & RM= Bluff Creek Trib,Reach-1,15920
     360     514     643     401     799    1595    1249
River Rch & RM= Bluff Creek Trib,Reach-1,12112
     418     600     755     472     942    1879    1483
River Rch & RM= Bluff Creek Trib,Reach-1,6350
     615     900    1147     724    1445    2883    2327
Boundary for River Rch & Prof#=Bluff Creek Trib,Reach-1,1
Up Type=0
Dn Type=3
Dn Slope=0.005
Boundary for River Rch & Prof#=Bluff Creek Trib,Reach-1,2
Up Type=0
Dn Type=3
Dn Slope=0.005
Boundary for River Rch & Prof#=Bluff Creek Trib,Reach-1,3
Up Type=0
Dn Type=3
Dn Slope=0.005
Boundary for River Rch & Prof#=Bluff Creek Trib,Reach-1,4
Up Type=0
Dn Type=3
Dn Slope=0.005
Boundary for River Rch & Prof#=Bluff Creek Trib,Reach-1,5
Up Type=0
Dn Type=3
Dn Slope=0.005
Boundary for River Rch & Prof#=Bluff Creek Trib,Reach-1,6
Up Type=0
Dn Type=3
Dn Slope=0.005
Boundary for River Rch & Prof#=Bluff Creek Trib,Reach-1,7
Up Type=0
Dn Type=3
Dn Slope=0.005

--- Bluff Creek Trib2.g01 (geometry) ---

Geom Title=Existing Conditions
Program Version=4.10

River Reach=Bluff Creek Trib,Reach-1
Reach XY= 30
        1406355.        6897238.        1406255.        6897088.
        1405605.        6896988.        1405655.        6896238.
        1405955.        6895738.        1405905.        6895288.
        1406205.        6895188.        1406305.        6894488.
      1406953.34      6893581.95      1406901.39      6893089.03
      1406713.02       6892934.7      1406860.59      6892642.79
      1407099.58      6892590.68       1407355.4        6891613.
      1407352.94      6891043.85      1407105.98      6890598.28
      1407545.88      6890444.76      1407305.01      6890003.41
      1407655.07      6889606.12      1407498.95      6889439.58
      1407210.34      6889490.74      1407251.47      6888939.46
      1406660.45      6888490.47      1406525.13      6887757.77
      1405749.07      6887390.23      1405360.42      6887490.75
      1405054.57      6886708.18      1405112.73       6886381.5
       1405503.9      6886077.45        1405305.        6885488.

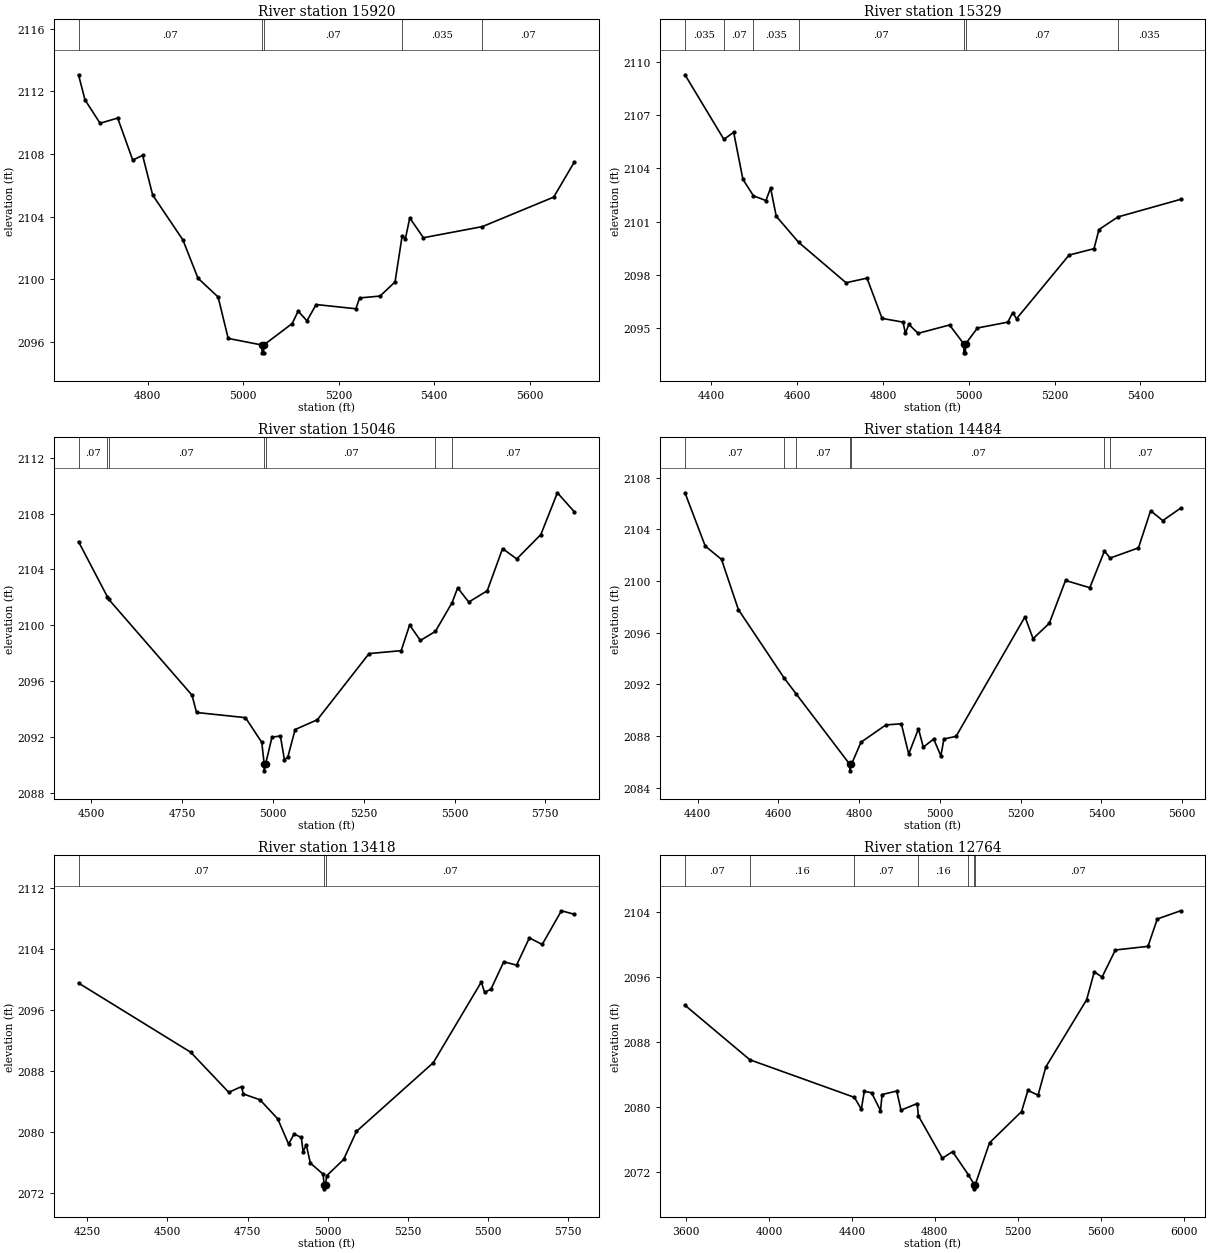
Type RM Length L Ch R = 1 ,15920   ,591,591,591
BEGIN DESCRIPTION:
Bluff Creek Trib2 30.0
END DESCRIPTION:
XS GIS Cut Line= 3
      1405982.37      6896797.51        1405655.        6896688.
      1404979.21      6896842.83
#Sta/Elev= 30
  4654.8 2113.05  4668.4 2111.45    4700 2109.96  4736.9 2110.29  4768.4 2107.61
  4789.1 2107.91  4810.2 2105.38  4873.5 2102.52  4905.1 2100.08  4947.3 2098.88
  4968.4 2096.24    5039 2095.82  5039.3 2095.32  5042.8 2095.32    5043 2095.82
  5102.6 2097.19    5115 2097.98  5133.4 2097.36  5152.7  2098.4    5236 2098.13
  5243.7 2098.82  5286.6 2098.94    5318 2099.84  5332.8 2102.76  5339.8 2102.61
  5348.8 2103.92  5377.5 2102.66  5501.1 2103.37  5650.4 2105.25  5693.3 2107.47
#Mann= 5 ,-1 , 0
  4654.8     .07       0    5039     .07       0    5043     .07       0
  5332.8    .035       0  5501.1     .07       0
Bank Sta=5039,5043
XS Rating Curve= 0 ,0
Exp/Cntr=0.3,0.1

Type RM Length L Ch R = 1 ,15329   ,283,283,283
BEGIN DESCRIPTION:
Bluff Creek Trib2 29.0
END DESCRIPTION:
XS GIS Cut Line= 3
      1406370.66      6896379.69        1405755.        6896138.
      1405266.96      6896062.78
#Sta/Elev= 30
  4338.6 2109.27  4429.3 2105.63  4452.1 2106.03  4473.6 2103.38  4498.2 2102.45
  4527.3 2102.18  4538.1 2102.89  4551.3  2101.3  4603.4 2099.83    4714 2097.55
  4762.8 2097.81    4798 2095.54  4846.9 2095.33  4852.2  2094.7  4860.3  2095.2
    4882  2094.7  4955.3 2095.17  4988.5  2094.1  4988.7  2093.6  4992.2  2093.6
  4992.5  2094.1  5020.2    2095  5091.1 2095.33  5102.4 2095.87  5111.3 2095.52
  5233.8 2099.11  5291.9 2099.47  5303.5 2100.55  5347.8 2101.26  5493.8 2102.25
#Mann= 7 ,-1 , 0
  4338.6    .035       0  4429.3     .07       0  4498.2    .035       0
  4603.4     .07       0  4988.5     .07       0  4992.5     .07       0
  5347.8    .035       0
Bank Sta=4988.5,4992.5
XS Rating Curve= 0 ,0
Exp/Cntr=0.3,0.1

Type RM Length L Ch R = 1 ,15046   ,562,562,562
BEGIN DESCRIPTION:
Bluff Creek Trib2 28.0
END DESCRIPTION:
XS GIS Cut Line= 3
      1406335.43      6896174.75        1405855.        6895938.
      1405039.59      6895786.29
#Sta/Elev= 30
  4464.4 2105.99  4543.9 2102.04  4547.5 2101.86    4777 2094.99  4789.4 2093.75
  4924.2 2093.38  4969.1 2091.61  4975.7 2090.07    4976 2089.57  4979.7 2090.07
  4997.2 2091.98  5020.3 2092.07  5031.5 2090.36  5040.7 2090.55    5061 2092.53
  5122.1 2093.23  5264.5 2097.97  5353.1 2098.18  5376.3 2100.02  5405.9 2098.91
  5447.3 2099.56  5493.2 2101.62  5508.6 2102.68  5539.1 2101.66    5590 2102.47
  5632.2 2105.49  5671.3 2104.75  5737.7  2106.5  5783.2 2109.49  5829.4 2108.14
#Mann= 7 ,-1 , 0
  4464.4     .07       0  4543.9    .035       0  4547.5     .07       0
  4975.7     .07       0  4979.7     .07       0  5447.3    .035       0
  5493.2     .07       0
Bank Sta=4975.7,4979.7
XS Rating Curve= 0 ,0
Exp/Cntr=0.3,0.1

Type RM Length L Ch R = 1 ,14484   ,1066,1066,1066
BEGIN DESCRIPTION:
Bluff Creek Trib2 27.0
END DESCRIPTION:
XS GIS Cut Line= 3
      1406500.32      6895648.69        1405905.        6895438.
      1405310.94      6895491.86
#Sta/Elev= 30
  4368.5 2106.82  4418.7  2102.7    4459 2101.67  4500.8 2097.79  4614.1  2092.5
  4643.7 2091.28  4776.9 2085.82  4777.1 2085.32  4780.9 2085.82  4804.5 2087.53
  4866.3 2088.87  4904.5 2088.96  4922.8 2086.62    4947 2088.57    4959 2087.15
  4984.6 2087.78  5002.5 2086.48    5010 2087.78  5040.2 2087.99  5210.9 2097.23
  5230.9 2095.54  5271.1 2096.73  5311.3 2100.04  5371.5 2099.48  5407.8 2102.32
  5421.7 2101.77    5492 2102.56  5522.1 2105.43  5552.3 2104.67  5596.5 2105.63
#Mann= 7 ,-1 , 0
  4368.5     .07       0  4614.1     .16       0  4643.7     .07       0
  4776.9     .07       0  4780.9     .07       0  5407.8    .035       0
  5421.7     .07       0
Bank Sta=4776.9,4780.9
XS Rating Curve= 0 ,0
Exp/Cntr=0.3,0.1

Type RM Length L Ch R = 1 ,13418   ,654,654,654
BEGIN DESCRIPTION:
Bluff Creek Trib2 26.0
END DESCRIPTION:
XS GIS Cut Line= 3
      1406641.56      6895438.99        1406305.        6894738.
       1405535.2      6894740.53
#Sta/Elev= 30
  4222.4  2099.5  4572.7 2090.42  4691.5 2085.16  4731.3 2085.92  4736.8 2084.95
  4789.2 2084.18  4844.5 2081.67  4878.2 2078.37  4895.3 2079.69    4918 2079.24
  4923.5 2077.38  4933.4 2078.27  4946.2 2075.88  4985.9 2074.43  4989.5    2073
  4989.7  2072.5  4993.5    2073  4997.2 2074.22    5050 2076.35    5090 2080.03
    5330 2089.05    5480 2099.64    5490 2098.28    5510 2098.69    5550 2102.29
    5590 2101.85    5630 2105.42    5670 2104.56    5730 2108.98  5769.8 2108.53
#Mann= 3 ,-1 , 0
  4222.4     .07       0  4989.5     .07       0  4993.5     .07       0
Bank Sta=4989.5,4993.5
XS Rating Curve= 0 ,0
Exp/Cntr=0.3,0.1

Type RM Length L Ch R = 1 ,12764   ,652,652,652
BEGIN DESCRIPTION:
Bluff Creek Trib2 25.0
END DESCRIPTION:
XS GIS Cut Line= 3
      1407638.24       6895082.3        1406555.        6894188.
      1405629.29      6893849.97
#Sta/Elev= 30
  3595.3 2092.55  3908.2 2085.82  4412.5 2081.18  4445.6 2079.71    4460 2081.93
  4495.1 2081.75  4538.1 2079.55    4546 2081.53  4616.3 2081.96  4637.1  2079.6
  4715.3 2080.42  4720.8  2078.9  4836.5 2073.67    4886 2074.48  4961.4 2071.64
  4990.8 2070.39  4991.1 2069.89  4994.8 2070.39  5063.9 2075.57  5218.4 2079.43
    5249 2082.04  5298.1 2081.45  5335.3 2084.93  5532.3 2093.23    5569 2096.66
  5606.8 2096.03  5670.7 2099.37    5828 2099.82    5873  2103.2  5985.5 2104.21
#Mann= 7 ,-1 , 0
  3595.3     .07       0  3908.2     .16       0  4412.5     .07       0
  4720.8     .16       0  4961.4     .07       0  4990.8     .07       0
  4994.8     .07       0
Bank Sta=4990.8,4994.8
XS Rating Curve= 0 ,0
Exp/Cntr=0.3,0.1

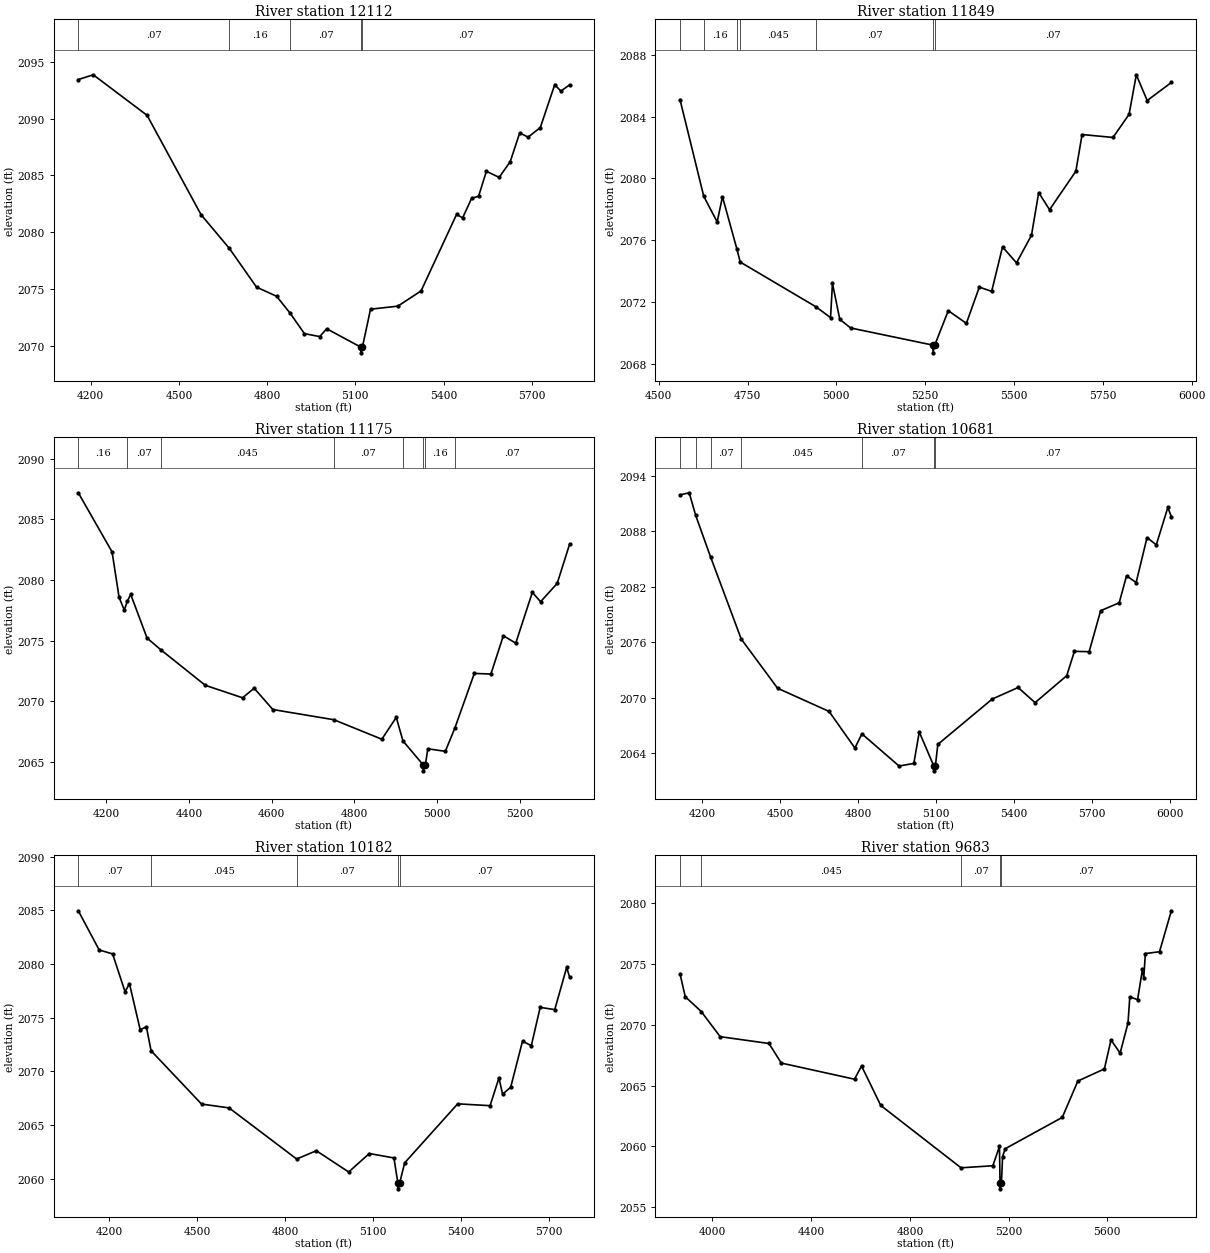
Type RM Length L Ch R = 1 ,12112   ,263,263,263
BEGIN DESCRIPTION:
Bluff Creek Trib2 24.0
END DESCRIPTION:
XS GIS Cut Line= 3
      1407673.14      6893937.31      1406875.05      6893668.02
      1406054.98        6893788.
#Sta/Elev= 30
  4157.7 2093.44  4208.5 2093.86  4391.7 2090.29  4575.2 2081.55  4671.5 2078.58
    4764 2075.17  4832.2 2074.37  4878.5 2072.87  4926.7 2071.08  4978.9 2070.82
  5002.6 2071.51  5118.7 2069.89  5119.1 2069.39    5124 2069.89  5151.6 2073.23
  5244.7  2073.5  5323.5 2074.84  5444.3 2081.57  5464.9 2081.27  5495.3 2082.98
  5519.2 2083.18  5545.8 2085.37  5589.1 2084.83  5626.7 2086.21  5659.1 2088.75
  5687.3 2088.37    5729 2089.21  5778.2    2093  5798.9 2092.42  5828.8 2092.98
#Mann= 5 ,-1 , 0
  4157.7     .07       0  4671.5     .16       0  4878.5     .07       0
  5118.7     .07       0    5124     .07       0
Bank Sta=5118.7,5124
XS Rating Curve= 0 ,0
Exp/Cntr=0.3,0.1

Type RM Length L Ch R = 1 ,11849   ,674,674,674
BEGIN DESCRIPTION:
Bluff Creek Trib2 23.0
END DESCRIPTION:
XS GIS Cut Line= 3
      1407354.97      6893587.99      1406934.46      6893458.15
      1406008.16      6893282.52
#Sta/Elev= 30
  4559.9  2085.1  4626.7 2078.84  4664.5 2077.18  4679.4 2078.81  4719.7 2075.45
  4729.4 2074.58  4942.7 2071.68  4983.6 2070.98    4989  2073.2  5009.6 2070.87
  5040.2 2070.31  5271.6  2069.2    5272  2068.7  5276.9  2069.2    5315 2071.43
  5365.9 2070.61  5402.4 2072.96  5437.1 2072.68  5467.6 2075.56    5507 2074.53
  5549.1 2076.31  5569.5 2079.08    5600 2077.97    5674 2080.46  5691.6 2082.84
  5778.6 2082.65  5823.9 2084.15  5844.2 2086.71  5874.8 2085.04  5942.8 2086.21
#Mann= 7 ,-1 , 0
  4559.9     .07       0  4626.7     .16       0  4719.7     .07       0
  4729.4    .045       0  4942.7     .07       0  5271.6     .07       0
  5276.9     .07       0
Bank Sta=5271.6,5276.9
XS Rating Curve= 0 ,0
Exp/Cntr=0.3,0.1

Type RM Length L Ch R = 1 ,11175   ,494,494,494
BEGIN DESCRIPTION:
Bluff Creek Trib2 22.0
END DESCRIPTION:
XS GIS Cut Line= 3
      1407505.01        6893338.      1406724.67      6892957.88
      1406404.98        6892938.
#Sta/Elev= 30
    4132  2087.2  4213.7 2082.32  4230.7 2078.56  4243.2 2077.52  4250.7 2078.26
  4258.8 2078.81  4298.3 2075.21  4331.7 2074.24  4439.1 2071.31  4529.3 2070.28
  4557.4 2071.07  4602.4 2069.31  4749.9 2068.47  4866.1 2066.86    4901 2068.66
  4917.2 2066.72  4965.9 2064.75  4966.3 2064.25  4971.4 2064.75  4977.4 2066.07
  5019.7 2065.86  5042.6 2067.77  5089.8 2072.29  5129.9 2072.24    5160  2075.4
    5190 2074.79  5230.1 2078.98  5250.1 2078.21  5290.2 2079.72  5320.3 2082.96
#Mann= 8 ,-1 , 0
    4132     .16       0  4250.7     .07       0  4331.7    .045       0
  4749.9     .07       0  4917.2     .16       0  4965.9     .07       0
  4971.4     .16       0  5042.6     .07       0
Bank Sta=4965.9,4971.4
XS Rating Curve= 0 ,0
Exp/Cntr=0.3,0.1

Type RM Length L Ch R = 1 ,10681   ,499,499,499
BEGIN DESCRIPTION:
Bluff Creek Trib2 21.0
END DESCRIPTION:
XS GIS Cut Line= 3
      1407605.03      6893288.03      1406971.54      6892671.32
        1406155.        6892088.
#Sta/Elev= 30
  4115.9 2091.91  4151.3 2092.14  4176.1  2089.7  4233.1 2085.22  4351.1 2076.33
  4490.8 2071.01  4688.7  2068.5  4787.7 2064.55  4814.8 2066.08  4957.4  2062.6
  5014.2 2062.88  5035.1 2066.28  5091.3 2062.58  5091.7 2062.08  5096.9 2062.58
  5106.4 2064.94  5315.3 2069.84  5414.9 2071.09    5480 2069.45  5601.7 2072.37
  5631.1    2075  5687.7 2074.96  5731.9 2079.39  5803.2 2080.25  5831.4 2083.16
  5868.3 2082.44  5910.1  2087.3  5945.7 2086.51    5990 2090.55  6003.5 2089.57
#Mann= 7 ,-1 , 0
  4115.9     .07       0  4176.1     .16       0  4233.1     .07       0
  4351.1    .045       0  4814.8     .07       0  5091.3     .07       0
  5096.9     .07       0
Bank Sta=5091.3,5096.9
XS Rating Curve= 0 ,0
Exp/Cntr=0.3,0.1

Type RM Length L Ch R = 1 ,10182   ,499,499,499
BEGIN DESCRIPTION:
Bluff Creek Trib2 20.0
END DESCRIPTION:
XS GIS Cut Line= 3
      1407655.01      6893038.01      1407171.98      6892271.39
        1406405.        6892188.
#Sta/Elev= 30
  4093.9 2084.95  4165.2  2081.3    4211 2080.93  4253.4 2077.42  4268.7 2078.14
  4305.2 2073.87  4326.4 2074.13  4342.4 2071.91  4514.7 2066.94  4608.9 2066.58
  4839.4 2061.82  4906.7 2062.59  5017.1 2060.61  5087.5 2062.33  5171.6 2061.92
  5185.3 2059.54  5185.7 2059.04  5190.9 2059.54  5208.2 2061.46  5389.3 2066.96
  5499.9 2066.79  5530.1 2069.37  5542.7 2067.86  5570.3 2068.51  5610.6  2072.8
  5640.7 2072.38  5670.9 2075.95  5720.7 2075.74  5761.4 2079.67  5771.5 2078.76
#Mann= 5 ,-1 , 0
  4093.9     .07       0  4342.4    .045       0  4839.4     .07       0
  5185.3     .07       0  5190.9     .07       0
Bank Sta=5185.3,5190.9
XS Rating Curve= 0 ,0
Exp/Cntr=0.3,0.1

Type RM Length L Ch R = 1 ,9683    ,91,91,91
BEGIN DESCRIPTION:
Bluff Creek Trib2 19.0
END DESCRIPTION:
XS GIS Cut Line= 3
      1408055.01      6892688.01      1407271.94      6891871.53
        1406455.        6892138.
#Sta/Elev= 30
  3868.7  2074.2  3889.9 2072.31  3954.8 2071.09  4031.5 2069.02  4229.3 2068.46
    4279 2066.85  4575.8 2065.52  4604.1 2066.61  4682.1 2063.36  5007.3 2058.23
  5136.3  2058.4  5162.9 2059.99  5165.3    2057  5165.8  2056.5    5171    2057
  5175.6 2059.16  5186.1  2059.8  5417.5 2062.38  5480.6 2065.37  5588.1 2066.37
  5614.8 2068.75  5651.9 2067.67  5683.8 2070.15    5691 2072.29  5722.6 2072.07
  5742.4 2074.58  5747.6 2073.87  5754.1 2075.86  5811.4 2076.01  5859.3 2079.38
#Mann= 5 ,-1 , 0
  3868.7     .07       0  3954.8    .045       0  5007.3     .07       0
  5165.3    .045       0    5171     .07       0
Bank Sta=5165.3,5171
XS Rating Curve= 0 ,0
Exp/Cntr=0.3,0.1

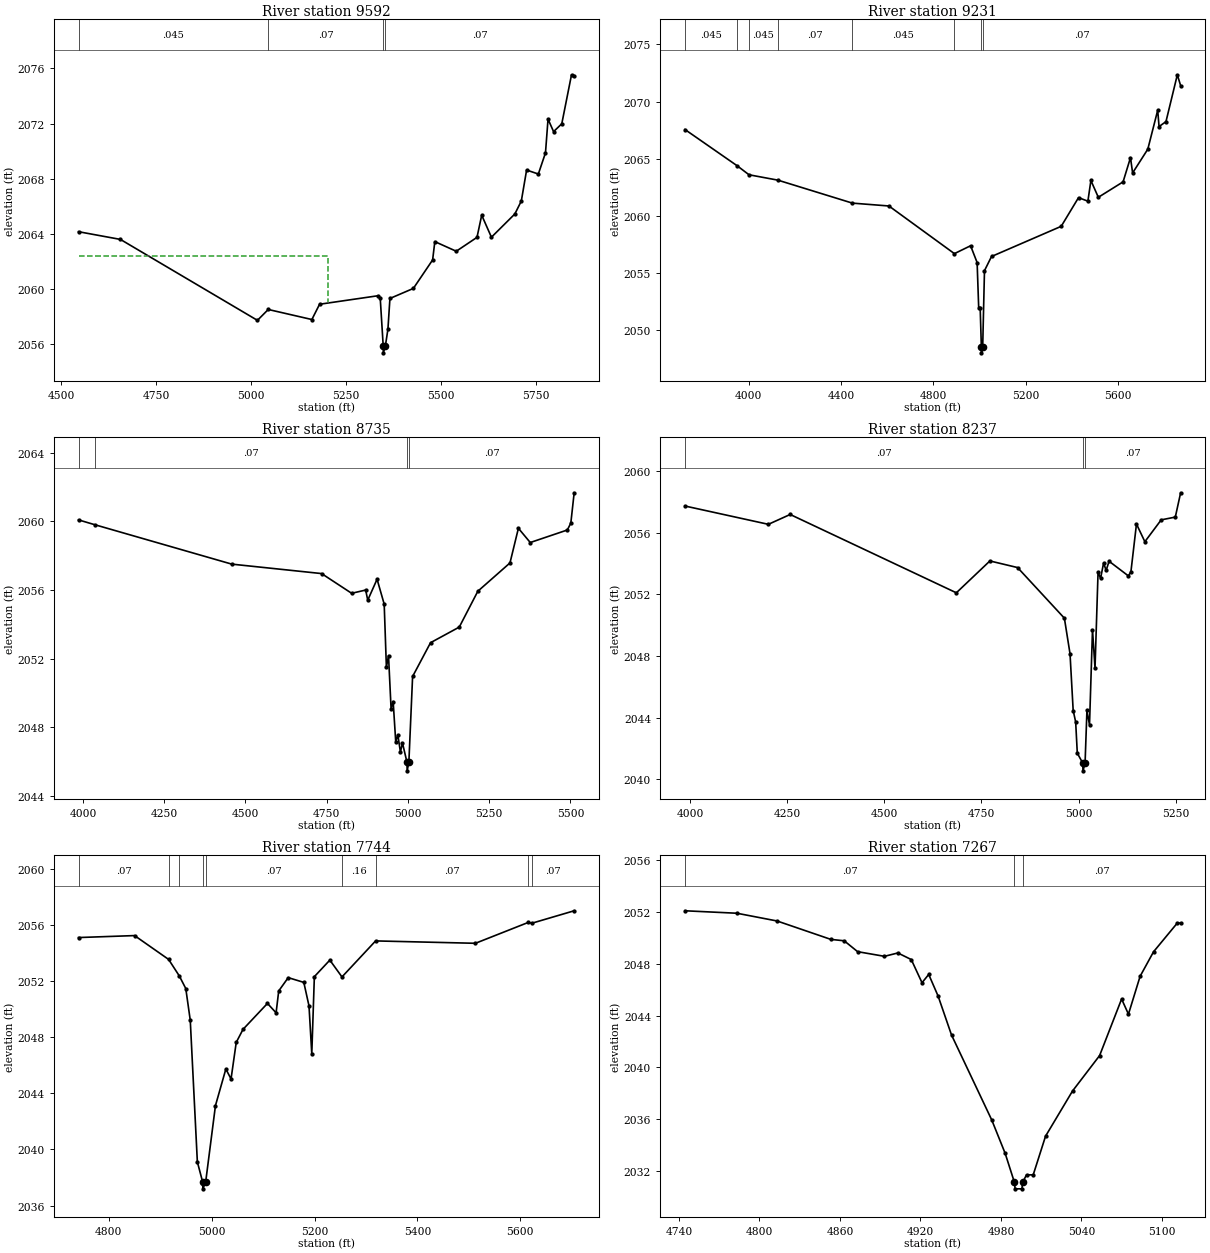
Type RM Length L Ch R = 1 ,9592    ,361,361,361
BEGIN DESCRIPTION:
Bluff Creek Trib2 4129
END DESCRIPTION:
XS GIS Cut Line= 3
      1407632.03      6892106.99      1407206.65       6891696.8
      1406533.89      6891935.53
#Sta/Elev= 30
  4546.2 2064.14  4656.5 2063.58  5017.2  2057.7  5045.7 2058.49  5160.5 2057.76
  5180.8 2058.87  5335.1 2059.49  5340.5  2059.3  5348.3 2055.84  5348.7 2055.34
    5354 2055.84  5360.7 2057.05    5366 2059.29  5427.7 2060.02  5478.4 2062.09
  5484.2 2063.42  5540.6 2062.72  5595.2 2063.73  5607.6 2065.34  5633.2 2063.74
  5694.9 2065.43  5711.9 2066.37  5725.8 2068.62  5756.7 2068.33  5775.5 2069.87
  5782.2 2072.32  5796.8 2071.41  5818.4 2071.98    5844 2075.54    5851 2075.42
#Mann= 4 ,-1 , 0
  4546.2    .045       0  5045.7     .07       0  5348.3    .045       0
    5354     .07       0
#XS Ineff= 2 , 0
         5202.25 2062.41
Permanent Ineff=
       F       F
Bank Sta=5348.3,5354
XS Rating Curve= 0 ,0
Exp/Cntr=0.3,0.1

Type RM Length L Ch R = 1 ,9231    ,496,496,496
BEGIN DESCRIPTION:
Bluff Creek Trib2 18.0
END DESCRIPTION:
XS GIS Cut Line= 3
      1408176.98      6892394.42      1407304.99        6891463.
      1406492.37       6891776.5
#Sta/Elev= 30
  3724.1 2067.55    3950 2064.38  4001.5 2063.59  4126.6 2063.12  4449.2 2061.11
  4607.5 2060.86  4891.1 2056.69  4961.2 2057.38  4989.5 2055.91  4996.3 2051.97
  5002.7 2051.97  5007.9 2048.51  5008.3 2048.01  5013.6 2048.51  5021.4  2055.2
  5051.9 2056.44  5353.7 2059.08  5428.7 2061.59  5469.3 2061.28  5482.3 2063.09
  5514.5 2061.62  5621.7 2062.97  5653.8 2065.09    5663 2063.75  5728.8 2065.83
  5771.7 2069.24  5777.5 2067.81  5807.5 2068.24  5856.7 2072.34    5871 2071.39
#Mann= 8 ,-1 , 0
  3724.1    .045       0    3950     .07       0  4001.5    .045       0
  4126.6     .07       0  4449.2    .045       0  4891.1     .07       0
  5007.9     .07       0  5013.6     .07       0
Bank Sta=5007.9,5013.6
XS Rating Curve= 0 ,0
Exp/Cntr=0.3,0.1

Type RM Length L Ch R = 1 ,8735    ,498,498,498
BEGIN DESCRIPTION:
Bluff Creek Trib2 17.0
END DESCRIPTION:
XS GIS Cut Line= 3
      1408121.84      6891664.41      1407338.57      6891021.24
      1406855.02      6891187.99
#Sta/Elev= 30
  3986.5 2060.09  4036.3 2059.81  4458.1 2057.51  4734.4 2056.96  4826.9 2055.81
    4870    2056  4876.4 2055.41  4905.1 2056.63    4927 2055.18  4933.8  2051.5
  4940.3 2052.18  4948.2 2049.08  4954.6  2049.5  4962.5 2047.15    4969 2047.56
  4976.9 2046.56  4983.3 2047.08  4997.1 2045.96  4997.6 2045.46  5002.9 2045.96
  5014.4 2050.96  5069.6 2052.93    5158 2053.84  5215.1 2055.93    5314 2057.58
  5339.9  2059.6  5376.4 2058.77  5490.4  2059.5  5501.2  2059.9  5511.5 2061.67
#Mann= 4 ,-1 , 0
  3986.5    .035       0  4036.3     .07       0  4997.1     .07       0
  5002.9     .07       0
Bank Sta=4997.1,5002.9
XS Rating Curve= 0 ,0
Exp/Cntr=0.3,0.1

Type RM Length L Ch R = 1 ,8237    ,493,493,493
BEGIN DESCRIPTION:
Bluff Creek Trib2 16.0
END DESCRIPTION:
XS GIS Cut Line= 3
      1407904.96      6891237.97      1407104.54      6890617.75
        1406905.        6890788.
#Sta/Elev= 30
  3987.4 2057.75  4201.9 2056.56    4258  2057.2  4685.4 2052.11  4771.7 2054.18
  4842.9 2053.75  4963.3 2050.46  4977.8 2048.15  4985.9 2044.46  4992.3 2043.72
  4996.5 2041.69  5010.6 2041.04  5011.1 2040.54  5016.5 2041.04  5021.3 2044.47
  5027.9 2043.52  5035.6 2049.71  5042.1 2047.21  5049.9 2053.45  5056.4 2053.05
  5064.1 2054.04  5070.7 2053.57  5078.3 2054.16  5127.8 2053.21  5134.4 2053.47
  5148.7 2056.58  5170.3 2055.43  5212.3 2056.85  5248.6 2057.03  5262.3 2058.61
#Mann= 3 ,-1 , 0
  3987.4     .07       0  5010.6     .07       0  5016.5     .07       0
Bank Sta=5010.6,5016.5
XS Rating Curve= 0 ,0
Exp/Cntr=0.3,0.1

Type RM Length L Ch R = 1 ,7744    ,477,477,477
BEGIN DESCRIPTION:
Bluff Creek Trib2 15.0
END DESCRIPTION:
XS GIS Cut Line= 3
      1407714.27      6890640.32      1407502.18      6890491.66
      1406805.04      6890388.01
#Sta/Elev= 30
    4741 2055.12    4850 2055.26  4916.2 2053.56    4937 2052.38  4949.6 2051.48
  4958.3 2049.22  4972.1 2039.11  4982.3 2037.69  4982.8 2037.19  4988.3 2037.69
  5007.3 2043.13  5027.5 2045.74  5037.6 2045.03  5047.7 2047.64  5060.9 2048.57
  5108.4 2050.42  5125.2 2049.75  5130.3 2051.31  5148.8 2052.26  5179.1 2051.92
  5189.2 2050.24  5194.6 2046.82  5199.6 2052.33  5229.7 2053.51  5253.3 2052.31
  5318.7 2054.88  5512.8 2054.71  5615.6  2056.2  5622.4 2056.14  5704.8 2057.03
#Mann= 9 ,-1 , 0
    4741     .07       0  4916.2     .16       0    4937     .07       0
  4982.3     .07       0  4988.3     .07       0  5253.3     .16       0
  5318.7     .07       0  5615.6     .16       0  5622.4     .07       0
Bank Sta=4982.3,4988.3
XS Rating Curve= 0 ,0
Exp/Cntr=0.3,0.1

Type RM Length L Ch R = 1 ,7267    ,425,425,425
BEGIN DESCRIPTION:
Bluff Creek Trib2 14.0
END DESCRIPTION:
XS GIS Cut Line= 3
      1407623.64      6890106.85       1407368.2      6890101.38
      1407254.99        6890088.
#Sta/Elev= 30
  4744.5 2052.11  4783.2 2051.92  4813.2 2051.32  4853.2  2049.9  4863.2 2049.79
  4873.2 2048.95  4893.2 2048.59  4903.2 2048.85  4913.2 2048.34  4921.2 2046.55
  4926.2 2047.19  4933.2 2045.52  4943.2 2042.51  4973.2 2035.94  4983.2 2033.36
  4990.1 2031.12  4990.6 2030.62  4995.7 2030.62  4996.2 2031.12  4999.1  2031.7
  5004.1  2031.7  5013.3 2034.69  5033.4 2038.18  5053.6 2040.92    5070 2045.29
  5075.1 2044.12  5083.8 2047.05  5093.8 2048.94  5111.5 2051.16    5114 2051.16
#Mann= 3 ,-1 , 0
  4744.5     .07       0  4990.1     .07       0  4996.2     .07       0
Bank Sta=4990.1,4996.2
XS Rating Curve= 0 ,0
Exp/Cntr=0.3,0.1

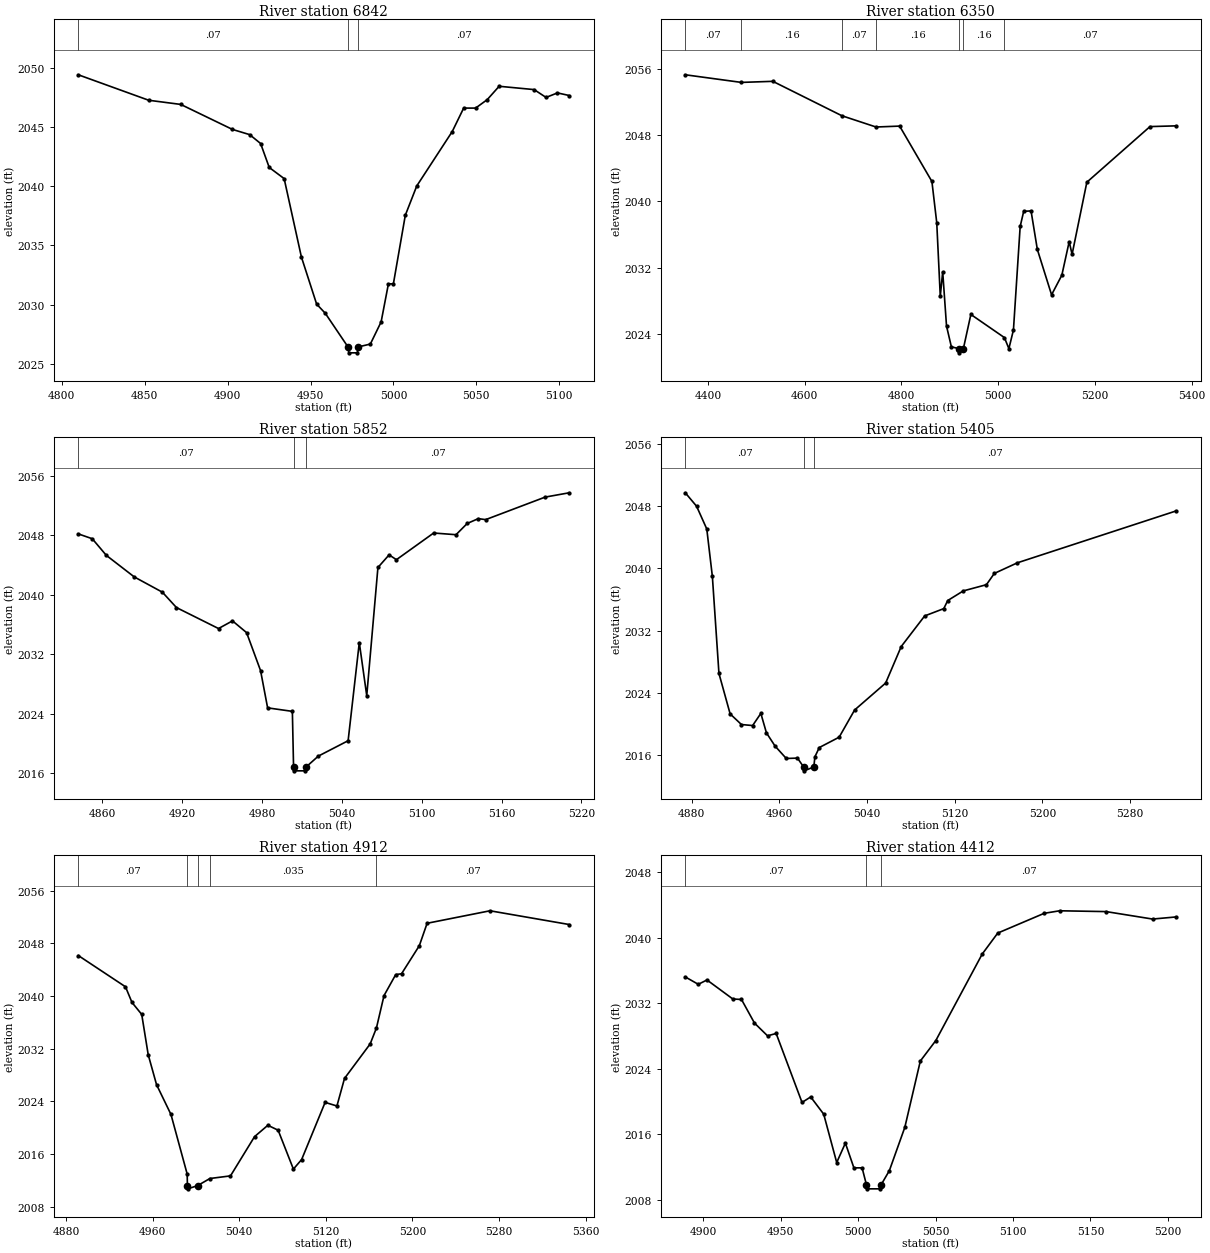
Type RM Length L Ch R = 1 ,6842    ,492,492,492
BEGIN DESCRIPTION:
Bluff Creek Trib2 13.0
END DESCRIPTION:
XS GIS Cut Line= 3
       1407530.7      6889947.41      1407478.33      6889764.66
      1407404.99      6889687.99
#Sta/Elev= 30
  4809.9  2049.4  4852.4 2047.25  4871.7  2046.9  4902.9 2044.79  4913.3 2044.35
  4919.9  2043.6  4925.1 2041.58  4934.1 2040.64  4944.5 2034.03  4953.7 2030.05
  4958.9 2029.28  4972.6 2026.44  4973.1 2025.94  4978.3 2025.94  4978.8 2026.44
  4986.1 2026.68  4992.6 2028.55    4997 2031.76    5000 2031.76  5007.2 2037.55
  5014.1 2040.02  5035.5 2044.61  5042.4 2046.59  5049.6 2046.59  5056.6  2047.3
  5063.8 2048.43  5084.9 2048.15  5092.1 2047.49    5099 2047.87  5106.1 2047.65
#Mann= 3 ,-1 , 0
  4809.9     .07       0  4972.6     .07       0  4978.8     .07       0
Bank Sta=4972.6,4978.8
XS Rating Curve= 0 ,0
Exp/Cntr=0.3,0.1

Type RM Length L Ch R = 1 ,6350    ,498,498,498
BEGIN DESCRIPTION:
Bluff Creek Trib2 12.0
END DESCRIPTION:
XS GIS Cut Line= 4
      1408141.31      6889513.49      1407498.95      6889439.58
        1407405.        6889588.      1407302.07       6889750.6
#Sta/Elev= 30
  4353.4 2055.27  4469.3 2054.35  4534.3 2054.48    4677 2050.33  4747.6 2048.97
  4796.4 2049.08  4863.1  2042.4  4873.1 2037.42  4880.4 2028.56  4885.4 2031.51
  4893.3 2024.96  4903.3 2022.46  4918.8 2022.23  4919.3 2021.73  4928.1 2022.23
  4943.6 2026.36  5012.9 2023.57  5022.2 2022.24  5031.6 2024.49  5045.5 2036.97
  5052.8  2038.8    5068 2038.85    5081  2034.2  5110.4 2028.73  5131.6 2031.09
  5146.8 2035.14  5152.8 2033.61  5183.3 2042.31  5313.8 2049.02  5368.1 2049.11
#Mann= 7 ,-1 , 0
  4353.4     .07       0  4469.3     .16       0    4677     .07       0
  4747.6     .16       0  4918.8     .07       0  4928.1     .16       0
  5012.9     .07       0
Bank Sta=4918.8,4928.1
XS Rating Curve= 0 ,0
Exp/Cntr=0.3,0.1

Type RM Length L Ch R = 1 ,5852    ,447,447,447
BEGIN DESCRIPTION:
Bluff Creek Trib2 11.0
END DESCRIPTION:
XS GIS Cut Line= 4
      1407354.97      6889288.01      1407204.98        6889338.
        1407105.        6889388.      1407016.36      6889432.33
#Sta/Elev= 30
  4841.9  2048.2  4852.4 2047.55    4863 2045.31    4884 2042.41  4905.1 2040.36
  4915.7 2038.29  4947.3 2035.47  4957.8  2036.5  4968.4 2034.92  4978.9 2029.81
  4984.2  2024.8  5002.8 2024.33  5003.7 2016.83  5004.2 2016.33  5012.5 2016.33
    5013 2016.83  5022.3 2018.31  5044.7 2020.38  5053.1 2033.58  5058.7 2026.44
  5067.1 2043.68  5075.5 2045.38    5081 2044.73    5109 2048.32  5125.8 2048.09
  5134.2  2049.6  5142.5 2050.25  5148.1 2050.12  5192.8 2053.15  5210.9 2053.73
#Mann= 3 ,-1 , 0
  4841.9     .07       0  5003.7     .07       0    5013     .07       0
Bank Sta=5003.7,5013
XS Rating Curve= 0 ,0
Exp/Cntr=0.3,0.1

Type RM Length L Ch R = 1 ,5405    ,493,493,493
BEGIN DESCRIPTION:
Bluff Creek Trib2 10.0
END DESCRIPTION:
XS GIS Cut Line= 4
      1407355.02        6888888.      1407232.14      6888914.47
        1407155.        6888988.      1406999.06      6889136.64
#Sta/Elev= 30
  4874.3 2049.74  4884.6 2048.01  4893.9 2045.08    4899 2038.97    4905 2026.48
  4915.2 2021.28  4925.5 2019.91  4935.7 2019.78  4943.2 2021.34  4948.3 2018.84
  4956.2 2017.13  4966.4 2015.54  4976.6 2015.59  4982.2 2014.45  4982.7 2013.95
  4991.5 2014.45  4992.5 2015.76  4996.5 2016.95  5014.6 2018.28  5028.7 2021.78
    5057 2025.25  5071.2 2029.95  5092.6 2033.89    5110 2034.83  5113.6 2035.87
  5127.8 2037.11  5148.9 2037.91  5156.1 2039.36  5177.2 2040.73    5322 2047.41
#Mann= 3 ,-1 , 0
  4874.3     .07       0  4982.2     .07       0  4991.5     .07       0
Bank Sta=4982.2,4991.5
XS Rating Curve= 0 ,0
Exp/Cntr=0.3,0.1

Type RM Length L Ch R = 1 ,4912    ,500,500,500
BEGIN DESCRIPTION:
Bluff Creek Trib2 9.0
END DESCRIPTION:
XS GIS Cut Line= 4
      1406955.04      6888537.97      1406864.78      6888598.54
        1406655.        6888688.      1406547.61       6888733.8
#Sta/Elev= 30
  4891.3 2046.16  4934.9 2041.41  4940.9 2039.03  4949.9 2037.21  4955.9 2031.08
  4963.6 2026.53  4976.9 2022.01  4991.9 2012.94  4992.1  2011.2  4992.6  2010.7
  5001.6  2011.2  5012.9 2012.27  5031.9 2012.67  5054.1 2018.63  5066.4 2020.36
  5075.9 2019.61    5090  2013.7  5097.6 2015.15  5119.3 2023.84  5130.2 2023.29
  5137.2 2027.48  5160.9 2032.72  5166.7 2035.15  5173.7 2040.07  5184.5 2043.26
  5189.9 2043.39  5206.3 2047.65  5213.5 2051.06  5271.6 2052.96  5344.8 2050.87
#Mann= 5 ,-1 , 0
  4891.3     .07       0  4992.1     .07       0  5001.6     .07       0
  5012.9    .035       0  5166.7     .07       0
Bank Sta=4992.1,5001.6
XS Rating Curve= 0 ,0
Exp/Cntr=0.3,0.1

Type RM Length L Ch R = 1 ,4412    ,424,424,424
BEGIN DESCRIPTION:
Bluff Creek Trib2 8.0
END DESCRIPTION:
XS GIS Cut Line= 4
      1406754.98      6888188.01      1406655.08      6888237.97
        1406555.        6888238.      1406449.68      6888238.03
#Sta/Elev= 30
  4888.3  2035.2  4896.7  2034.3  4902.3 2034.83    4919 2032.51  4924.6 2032.45
    4933 2029.57  4941.4 2028.02    4947  2028.3  4963.7 2019.89  4969.3 2020.56
  4977.7 2018.46  4986.1 2012.56  4991.7 2014.93  4997.2 2011.91  5002.5 2011.91
  5005.3 2009.85  5005.8 2009.35  5014.3 2009.35  5014.8 2009.85  5020.1 2011.57
  5030.1 2016.86  5040.1 2024.94  5050.1 2027.44  5080.1    2038  5090.1 2040.55
  5120.1 2042.96  5130.1 2043.27  5160.1 2043.17  5190.1 2042.26  5205.4 2042.52
#Mann= 3 ,-1 , 0
  4888.3     .07       0  5005.3     .07       0  5014.8     .07       0
Bank Sta=5005.3,5014.8
XS Rating Curve= 0 ,0
Exp/Cntr=0.3,0.1

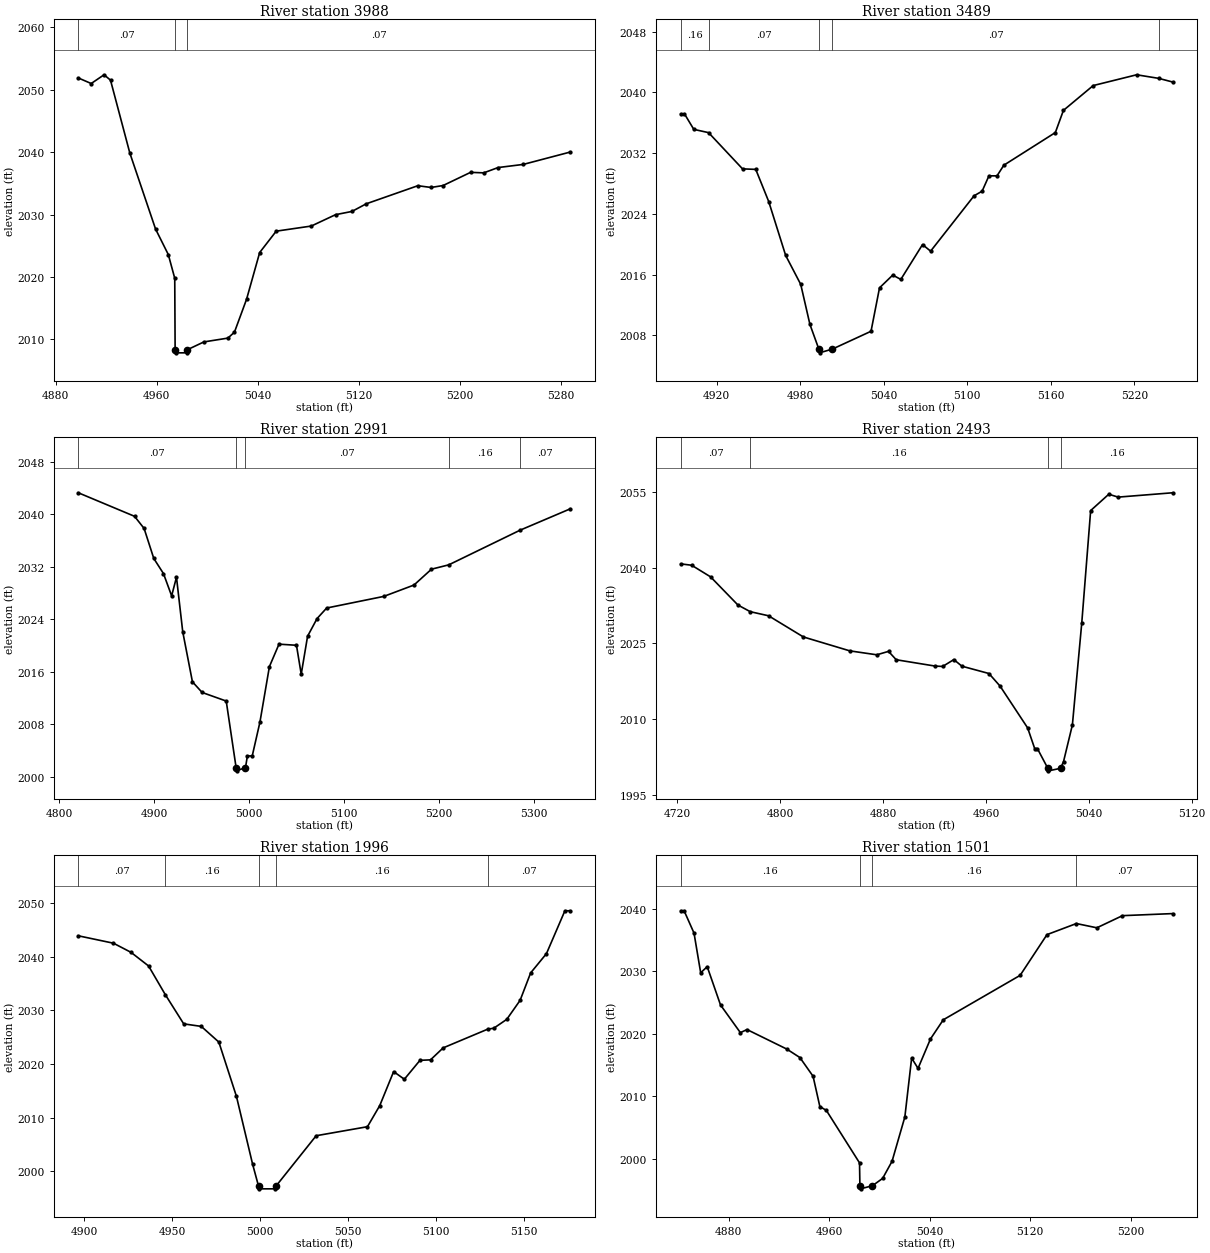
Type RM Length L Ch R = 1 ,3988    ,499,499,499
BEGIN DESCRIPTION:
Bluff Creek Trib2 7.0
END DESCRIPTION:
XS GIS Cut Line= 4
        1406705.        6887838.      1406604.88      6887858.05
        1406505.        6887888.       1406329.4      6887940.65
#Sta/Elev= 30
  4897.9 2051.89  4908.1    2051  4918.3  2052.4  4923.4 2051.54  4938.7 2039.87
  4959.1 2027.69  4969.2  2023.6  4974.3  2019.8  4974.6 2008.36  4975.1 2007.86
  4983.8 2007.86  4984.3 2008.36  4997.4 2009.61  5016.4 2010.22  5021.6 2011.17
  5031.2 2016.44  5041.6 2023.93  5054.7 2027.35  5082.5 2028.17  5101.7 2029.99
  5114.7 2030.51    5126 2031.73  5166.9 2034.63  5177.4 2034.35  5186.9 2034.66
  5208.7 2036.77  5219.1 2036.69  5230.5 2037.54  5250.4 2038.04  5287.6 2040.02
#Mann= 3 ,-1 , 0
  4897.9     .07       0  4974.6     .07       0  4984.3     .07       0
Bank Sta=4974.6,4984.3
XS Rating Curve= 0 ,0
Exp/Cntr=0.3,0.1

Type RM Length L Ch R = 1 ,3489    ,498,498,498
BEGIN DESCRIPTION:
Bluff Creek Trib2 6.0
END DESCRIPTION:
XS GIS Cut Line= 4
      1406255.01      6887487.97      1406215.62      6887586.17
        1406155.        6887688.      1406089.02      6887798.84
#Sta/Elev= 30
  4894.2 2037.16  4896.9 2037.16  4903.6 2035.12  4914.2 2034.69  4938.6 2029.92
  4948.1 2029.85  4957.4 2025.62  4969.6 2018.51  4980.4 2014.71    4987 2009.44
  4993.4 2006.19  4993.9 2005.69  5003.2 2006.19  5030.9 2008.53    5037 2014.25
  5046.5 2015.93  5052.3 2015.36  5067.9 2019.95  5073.7 2019.08  5104.9 2026.37
  5110.7 2026.98  5115.6    2029  5121.4    2029  5126.3  2030.4  5163.3  2034.7
  5169.1 2037.62  5190.5 2040.89  5221.7 2042.31  5237.5 2041.84  5247.5 2041.36
#Mann= 5 ,-1 , 0
  4894.2     .16       0  4914.2     .07       0  4993.4     .07       0
  5003.2     .07       0  5237.5     .16       0
Bank Sta=4993.4,5003.2
XS Rating Curve= 0 ,0
Exp/Cntr=0.3,0.1

Type RM Length L Ch R = 1 ,2991    ,498,498,498
BEGIN DESCRIPTION:
Bluff Creek Trib2 5.0
END DESCRIPTION:
XS GIS Cut Line= 4
       1405828.9      6887249.87      1405795.48      6887426.84
        1405805.        6887538.      1405824.32      6887763.61
#Sta/Elev= 30
  4819.9 2043.26  4879.1 2039.68  4889.2 2037.83  4899.4 2033.26  4909.6 2030.96
  4918.2 2027.57  4923.3 2030.41  4929.9  2022.1  4940.1 2014.49  4950.3 2012.87
  4975.7 2011.56  4986.1 2001.44  4986.6 2000.94    4996 2001.44    4998 2003.21
  5003.1 2003.21  5011.2 2008.35  5021.2 2016.81  5031.3 2020.22  5049.7 2020.05
  5054.7 2015.65  5061.4 2021.43  5071.4 2024.12  5081.5 2025.72  5141.7 2027.49
  5173.5 2029.22  5191.9 2031.63  5210.1 2032.29  5285.3 2037.57    5338 2040.81
#Mann= 5 ,-1 , 0
  4819.9     .07       0  4986.1     .07       0    4996     .07       0
  5210.1     .16       0  5285.3     .07       0
Bank Sta=4986.1,4996
XS Rating Curve= 0 ,0
Exp/Cntr=0.3,0.1

Type RM Length L Ch R = 1 ,2493    ,497,497,497
BEGIN DESCRIPTION:
Bluff Creek Trib2 4.0
END DESCRIPTION:
XS GIS Cut Line= 3
      1405530.98      6887280.93      1405377.72      6887512.15
      1405304.98      6887588.02
#Sta/Elev= 30
  4722.6 2040.77  4731.1  2040.5  4745.8  2038.2  4767.1 2032.61  4776.7 2031.29
  4790.9 2030.48    4818 2026.28  4854.1 2023.52  4875.1 2022.74  4884.2 2023.42
  4890.2 2021.76  4920.3 2020.51  4926.3 2020.43    4935 2021.79  4941.3 2020.48
  4962.3 2019.03    4971 2016.52  4992.4 2008.24  4997.9 2004.13    5000 2004.13
  5008.1 2000.23  5008.6 1999.73    5018 2000.23  5020.3 2001.56  5027.2 2008.84
  5034.5  2029.1  5041.4 2051.34  5055.5 2054.58  5062.8 2054.01  5105.1 2054.87
#Mann= 4 ,-1 , 0
  4722.6     .07       0  4776.7     .16       0  5008.1     .07       0
    5018     .16       0
Bank Sta=5008.1,5018
XS Rating Curve= 0 ,0
Exp/Cntr=0.3,0.1

Type RM Length L Ch R = 1 ,1996    ,495,495,495
BEGIN DESCRIPTION:
Bluff Creek Trib2 3.0
END DESCRIPTION:
XS GIS Cut Line= 3
      1405404.95        6887038.      1405301.46      6887039.46
      1405155.02      6887137.99
#Sta/Elev= 30
  4896.5 2043.88  4916.5  2042.5  4926.5  2040.8  4936.5 2038.26    4946 2032.93
  4956.5 2027.48  4966.5 2027.01  4976.5 2024.09  4986.5    2014  4995.7 2001.37
  4999.1 1997.26  4999.6 1996.76  5008.5 1996.76    5009 1997.26  5031.9 2006.65
  5061.1 2008.33  5068.1 2012.26    5076 2018.59  5082.1 2017.17    5091 2020.69
    5097 2020.78  5104.2 2023.01  5129.6  2026.5    5133 2026.67  5140.4 2028.32
    5148 2031.86    5154 2036.97    5163 2040.56  5173.5 2048.54  5176.5 2048.54
#Mann= 5 ,-1 , 0
  4896.5     .07       0    4946     .16       0  4999.1     .07       0
    5009     .16       0  5129.6     .07       0
Bank Sta=4999.1,5009
XS Rating Curve= 0 ,0
Exp/Cntr=0.3,0.1

Type RM Length L Ch R = 1 ,1501    ,496,496,496
BEGIN DESCRIPTION:
Bluff Creek Trib2 2.0
END DESCRIPTION:
XS GIS Cut Line= 3
      1405205.04      6886688.01      1405054.85        6886638.
      1404825.84      6886683.09
#Sta/Elev= 30
  4841.7 2039.66  4844.4 2039.66  4852.3 2036.09  4857.6 2029.75  4862.8 2030.73
  4873.4 2024.61  4889.2 2020.19  4894.5 2020.68  4926.1 2017.57  4936.6 2016.21
  4947.1 2013.22  4952.5 2008.38  4957.7 2007.76  4984.1 1999.38  4984.4 1995.73
  4984.9 1995.23  4994.4 1995.73  5002.5  1996.9    5010 1999.63  5020.2 2006.72
  5025.6 2016.12  5030.7 2014.48  5040.6 2019.18  5050.8 2022.24    5112 2029.34
  5133.4 2035.85  5156.8 2037.62  5173.1 2036.94  5193.5 2038.88  5233.4 2039.21
#Mann= 4 ,-1 , 0
  4841.7     .16       0  4984.4     .07       0  4994.4     .16       0
  5156.8     .07       0
Bank Sta=4984.4,4994.4
XS Rating Curve= 0 ,0
Exp/Cntr=0.3,0.1