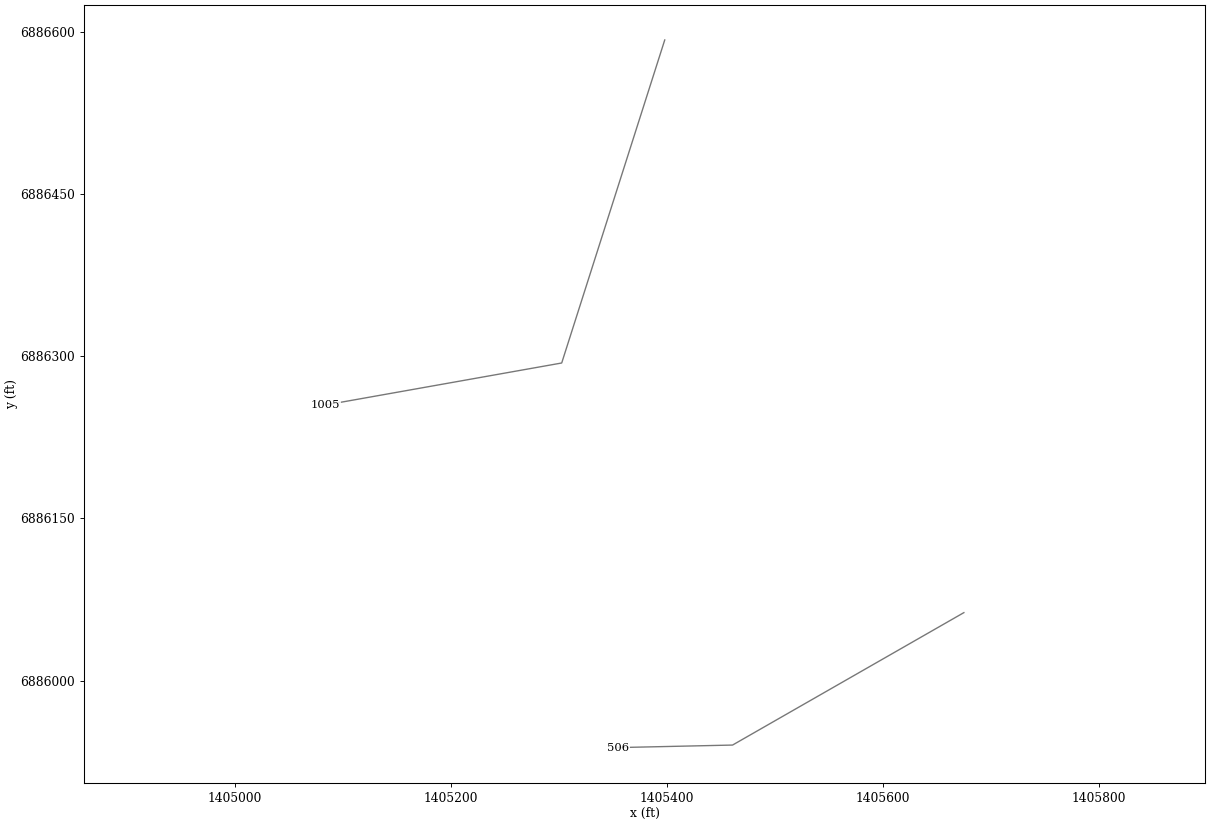
HEC-RAS study Bluff Creek Trib2.prj: Bluff Creek Trib2 Base Level Engineering

--- Bluff Creek Trib2.g01 (geometry) --- (continued)

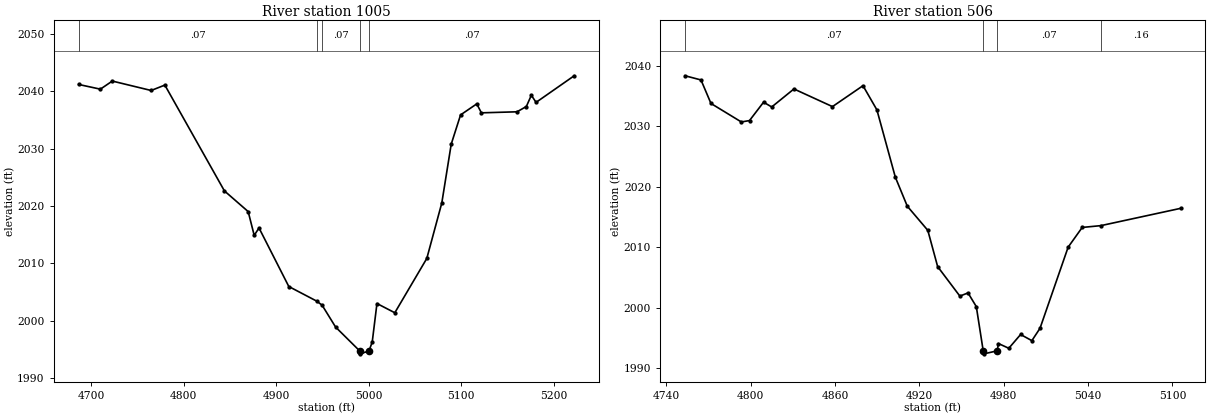
Type RM Length L Ch R = 1 ,1005    ,499,499,499
BEGIN DESCRIPTION:
Bluff Creek Trib2 1.0
END DESCRIPTION:
XS GIS Cut Line= 3
      1405398.02      6886592.67      1405302.69      6886293.81
      1405084.12      6886254.95
#Sta/Elev= 30
  4686.3 2041.15  4709.8 2040.33  4722.7 2041.74  4764.7  2040.1  4779.5 2041.04
  4843.9 2022.62  4869.6 2019.02  4876.1 2014.88  4881.3 2016.17  4913.5 2005.98
  4943.5 2003.45  4949.5 2002.73  4964.1 1998.92  4990.2 1994.76  4990.7 1994.26
  5000.2 1994.76  5003.7 1996.33  5008.8 2003.02  5028.1 2001.41  5062.7 2010.87
  5078.9 2020.52  5089.1 2030.77  5099.2 2035.85  5116.7 2037.77  5121.7 2036.21
  5160.2 2036.39  5170.3 2037.31  5175.7 2039.27  5180.8 2038.03    5222 2042.66
#Mann= 5 ,-1 , 0
  4686.3     .07       0  4943.5     .16       0  4949.5     .07       0
  4990.2     .07       0  5000.2     .07       0
Bank Sta=4990.2,5000.2
XS Rating Curve= 0 ,0
Exp/Cntr=0.3,0.1

Type RM Length L Ch R = 1 ,506     ,0,0,0
BEGIN DESCRIPTION:
Sweetwater Creek Trib 27 T3 35.0
END DESCRIPTION:
XS GIS Cut Line= 3
      1405674.77      6886062.85      1405460.76      6885940.33
      1405354.98        6885938.
#Sta/Elev= 30
  4753.4 2038.37  4764.7 2037.68  4771.8 2033.79  4793.4 2030.73  4799.2 2030.96
  4809.2    2034    4815 2033.21  4830.8 2036.19  4858.2 2033.27  4879.9 2036.73
  4889.8 2032.73  4902.9  2021.6  4911.4  2016.8    4926  2012.8    4933  2006.8
  4948.8 2001.92  4954.6 2002.45  4960.5 2000.18  4965.4 1992.87  4965.9 1992.37
  4975.4 1992.87  4976.2 1994.08  4983.6 1993.29    4992 1995.57    5000 1994.55
  5005.8  1996.6  5025.8 2010.02  5035.8 2013.28  5049.1 2013.58  5105.8 2016.44
#Mann= 4 ,-1 , 0
  4753.4     .07       0  4965.4     .07       0  4975.4     .07       0
  5049.1     .16       0
Bank Sta=4965.4,4975.4
XS Rating Curve= 0 ,0
Exp/Cntr=0.3,0.1

Chan Stop Cuts=-1
Use User Specified Reach Order=0
Composite Channel Slope=5