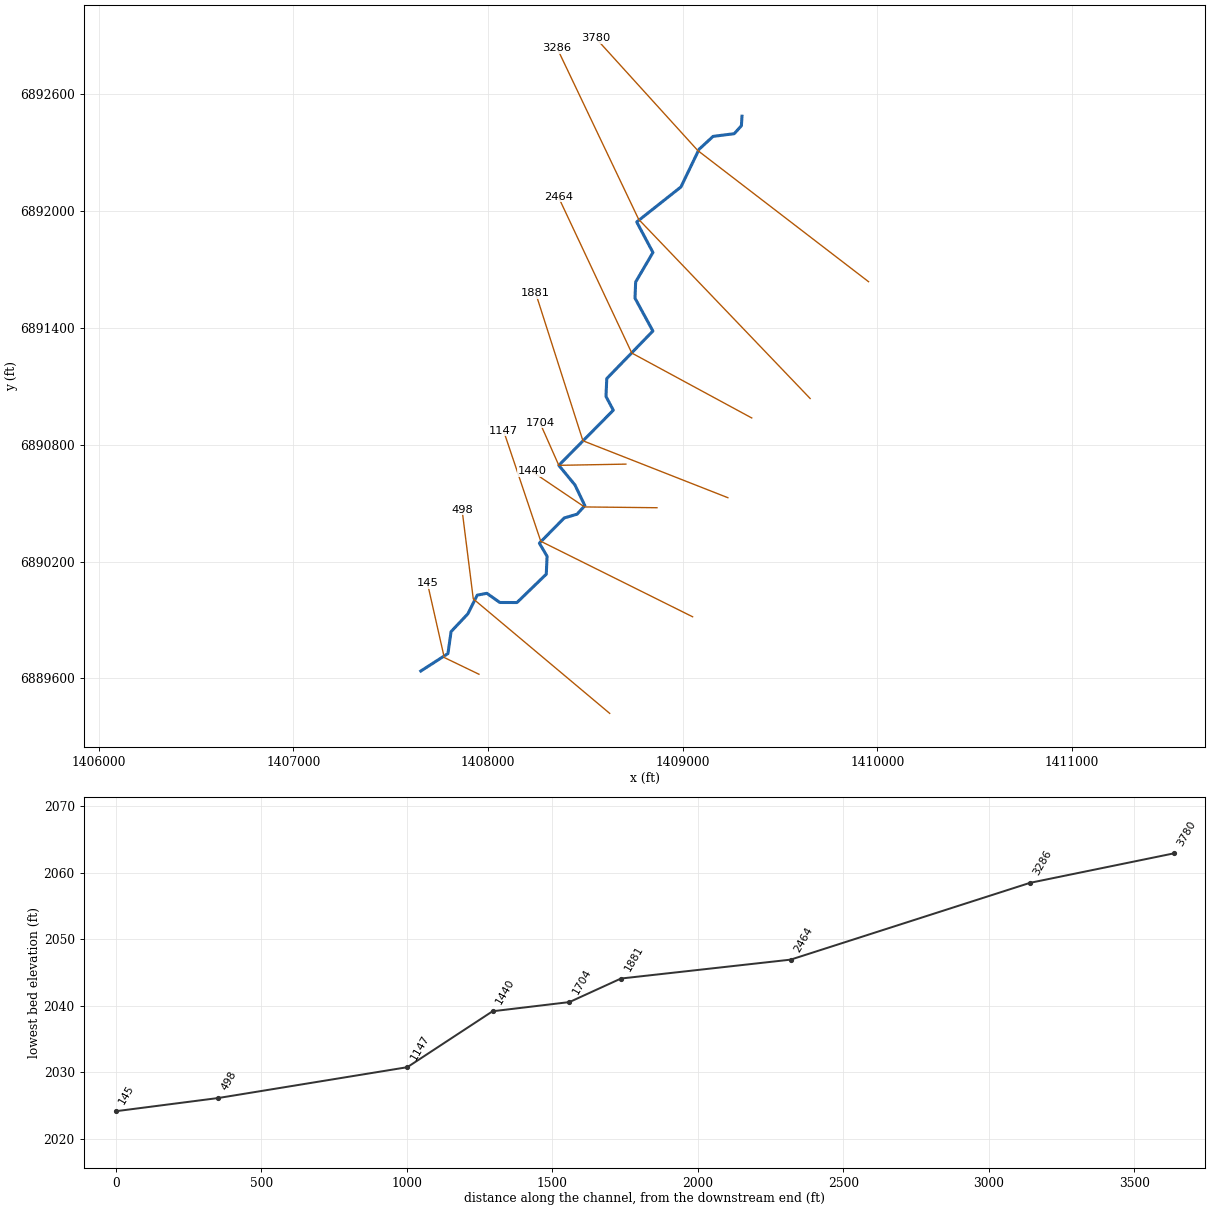
--- Bluff Creek Trib2T.prj (project) ---

Proj Title=Bluff Creek Trib2T Base Level Engineering
Current Plan=p01
Default Exp/Contr=0.3,0.1
English Units
Geom File=g01
Flow File=f01
Plan File=p01
Y Axis Title=Elevation
X Axis Title(PF)=Main Channel Distance
X Axis Title(XS)=Station
BEGIN DESCRIPTION:
Bluff Creek Trib2T
END DESCRIPTION:
DSS Export Rating Curves= 0
DSS Export Rating Curve Sorted= 0
DSS Export Volume Flow Curves= 0
DXF OffsetX= 0
DXF OffsetY= 0
DXF ScaleX= 1
DXF ScaleY= 10

--- Bluff Creek Trib2T.p01 (plan) ---

Plan Title=Multiple Run
Short Identifier=Multiple
Geom File=g01
Flow File=f01
Subcritical Flow
K Sum by GR= 0
Std Step Tol= 0.01
Critical Tol= 0.01
Num of Std Step Trials= 20
Max Error Tol= 0.3
Flow Tol Ratio= 0.001
Split Flow NTrial= 30
Split Flow Tol= 0.02
Split Flow Ratio= 0.02
Log Output Level= 0
Friction Slope Method= 1
Unsteady Friction Slope Method= 2
Unsteady Bridges Friction Slope Method= 1
Parabolic Critical Depth
Global Vel Dist=  1 , 1 , 1
Global Log Level= 0
CheckData=True
Encroach Param= -1, 0, 0, 0
BEGIN DESCRIPTION:
Multiple Run
END DESCRIPTION:

--- Bluff Creek Trib2T.f01 (steady flow) ---

Flow Title=Multiple
Number of Profiles=7
Profile Names=10-year,25-year,50-year,1pct_min,100-year,1pct_plu,500-year
River Rch & RM= Bluff Creek Trib,Reach-1,3780
     267     375     465     287     573    1144     881
River Rch & RM= Bluff Creek Trib,Reach-1,2464
     295     417     520     322     642    1282     995
Boundary for River Rch & Prof#=Bluff Creek Trib,Reach-1,1
Up Type=0
Dn Type=3
Dn Slope=0.005
Boundary for River Rch & Prof#=Bluff Creek Trib,Reach-1,2
Up Type=0
Dn Type=3
Dn Slope=0.005
Boundary for River Rch & Prof#=Bluff Creek Trib,Reach-1,3
Up Type=0
Dn Type=3
Dn Slope=0.005
Boundary for River Rch & Prof#=Bluff Creek Trib,Reach-1,4
Up Type=0
Dn Type=3
Dn Slope=0.005
Boundary for River Rch & Prof#=Bluff Creek Trib,Reach-1,5
Up Type=0
Dn Type=3
Dn Slope=0.005
Boundary for River Rch & Prof#=Bluff Creek Trib,Reach-1,6
Up Type=0
Dn Type=3
Dn Slope=0.005
Boundary for River Rch & Prof#=Bluff Creek Trib,Reach-1,7
Up Type=0
Dn Type=3
Dn Slope=0.005

--- Bluff Creek Trib2T.g01 (geometry) ---

Geom Title=Existing Conditions
Program Version=4.10

River Reach=Bluff Creek Trib,Reach-1
Reach XY= 30
        1409305.        6892488.      1409301.88      6892438.99
       1409265.1      6892398.26      1409156.49      6892384.39
      1409084.58      6892318.24      1408991.39      6892124.76
       1408764.1      6891944.75       1408847.5        6891788.
      1408758.67      6891636.42      1408755.37      6891553.27
      1408847.23      6891384.59       1408610.4      6891140.43
      1408606.27      6891048.48       1408643.9      6890977.94
      1408363.96      6890694.67      1408446.84      6890594.05
       1408497.8       6890487.7      1408457.85      6890443.85
      1408391.81      6890424.37      1408264.13      6890294.74
      1408303.73      6890227.52       1408299.6      6890135.57
      1408149.11      6889989.96      1408060.97      6889990.19
      1407994.24       6890037.3        1407945.      6890027.94
      1407896.81      6889931.98      1407810.54      6889840.42
      1407794.63      6889727.89        1407655.        6889638.

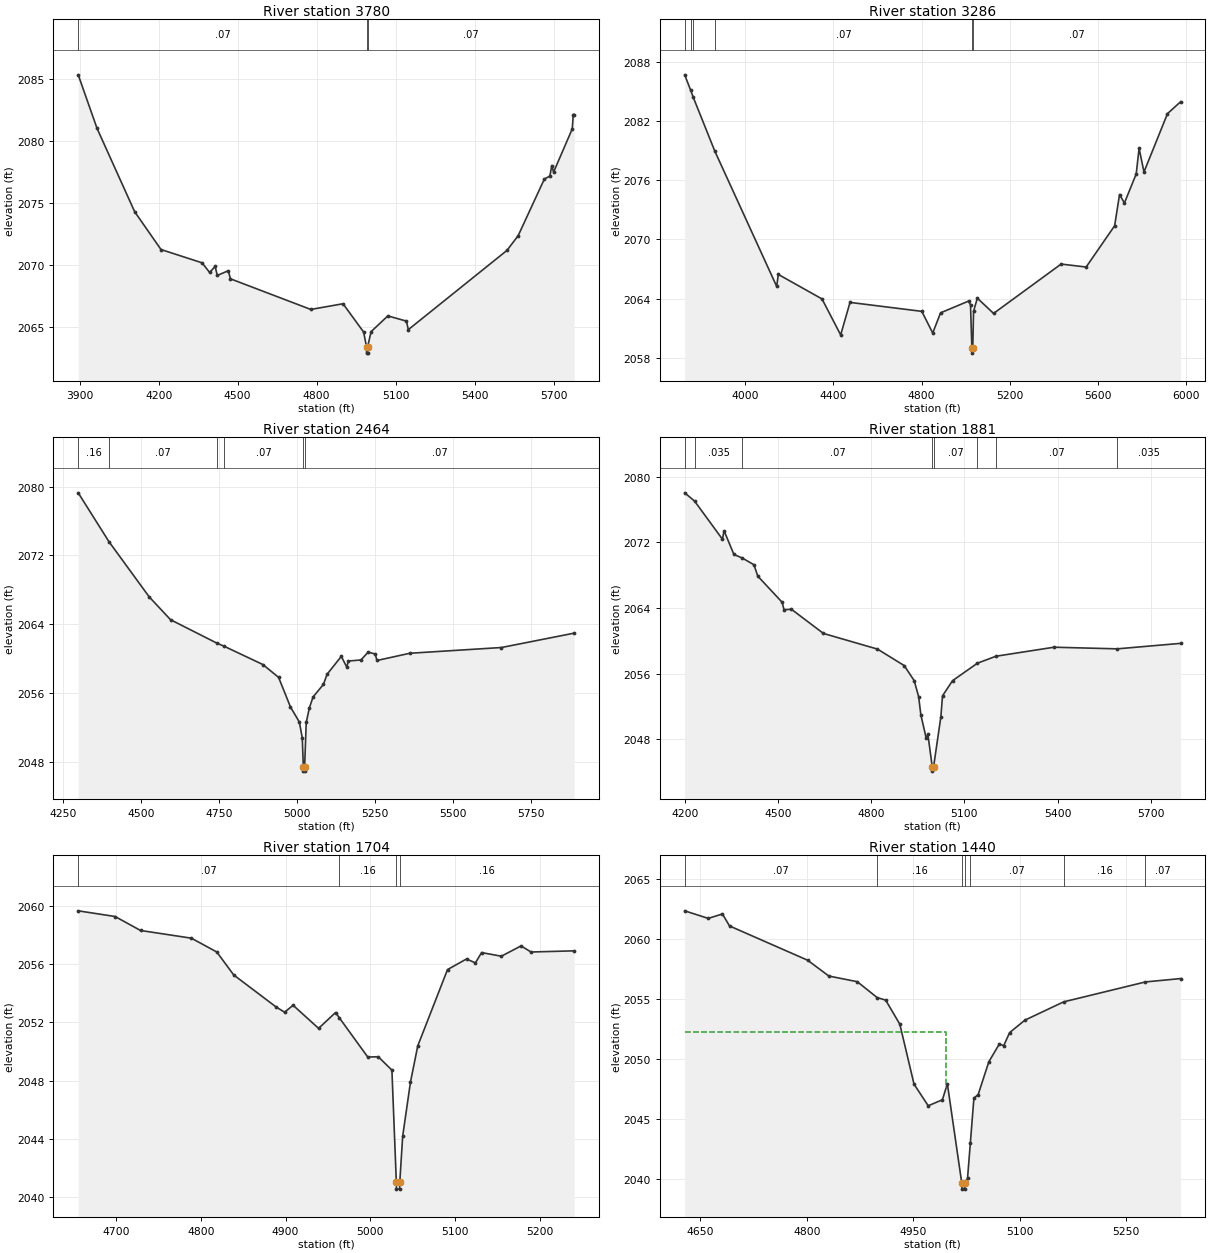
Type RM Length L Ch R = 1 ,3780    ,494,494,494
BEGIN DESCRIPTION:
Bluff Creek Trib2T 6.0
END DESCRIPTION:
XS GIS Cut Line= 3
        1409955.        6891638.      1409077.99      6892311.52
      1408554.97      6892888.03
#Sta/Elev= 30
  3894.2 2085.32  3965.8    2081  4108.6 2074.29  4208.7 2071.24  4364.6 2070.17
  4393.6 2069.39  4414.4 2069.88  4422.6 2069.15  4464.3 2069.53  4472.5 2068.88
  4777.8 2066.41  4900.3 2066.87  4978.5 2064.59  4989.7 2063.39    4990 2062.89
  4993.5 2062.89  4993.7 2063.39  5006.9 2064.62  5070.5 2065.89  5141.4 2065.47
  5148.2 2064.78  5523.2 2071.17  5565.8 2072.36  5665.2 2076.92  5686.1 2077.16
  5693.5 2078.01  5700.3 2077.48  5771.3 2080.97    5775 2082.12  5778.4 2082.12
#Mann= 3 ,-1 , 0
  3894.2     .07       0  4989.7     .07       0  4993.7     .07       0
Bank Sta=4989.7,4993.7
XS Rating Curve= 0 ,0
Exp/Cntr=0.3,0.1

Type RM Length L Ch R = 1 ,3286    ,822,822,822
BEGIN DESCRIPTION:
Bluff Creek Trib2T 5.0
END DESCRIPTION:
XS GIS Cut Line= 3
      1409655.02      6891037.98      1408774.27      6891958.07
        1408355.      6892837.99
#Sta/Elev= 30
  3726.3 2086.71  3753.1 2085.17  3764.6 2084.46    3863 2078.96  4143.5 2065.23
  4150.7 2066.45  4348.9 2063.96  4433.5 2060.31  4475.9 2063.61  4801.4  2062.7
  4850.8  2060.5  4886.4 2062.55  5013.2 2063.74  5022.1 2063.36  5028.4 2058.96
  5028.6 2058.46  5032.4 2058.96  5035.9  2062.7  5053.1 2064.04  5126.7 2062.49
  5432.9  2067.5  5546.4  2067.2  5675.6 2071.39  5697.8 2074.56  5719.9  2073.7
  5773.4 2076.65  5786.4 2079.25  5808.6 2076.85  5915.2 2082.77  5974.7 2083.98
#Mann= 6 ,-1 , 0
  3726.3     .16       0  3753.1     .07       0  3764.6     .16       0
    3863     .07       0  5028.4     .07       0  5032.4     .07       0
Bank Sta=5028.4,5032.4
XS Rating Curve= 0 ,0
Exp/Cntr=0.3,0.1

Type RM Length L Ch R = 1 ,2464    ,583,583,583
BEGIN DESCRIPTION:
Bluff Creek Trib2T 4.0
END DESCRIPTION:
XS GIS Cut Line= 3
      1409354.96      6890938.02      1408738.65      6891271.62
      1408361.42      6892074.29
#Sta/Elev= 30
  4299.2 2079.27  4397.7 2073.59  4526.6 2067.17  4594.8 2064.52  4743.5 2061.79
  4766.1 2061.44  4890.4 2059.31  4940.7 2057.82  4978.8 2054.37  5007.1 2052.63
  5016.5  2050.8  5019.9 2047.42  5020.2 2046.92  5023.8 2046.92    5024 2047.42
  5029.2 2052.58  5039.3 2054.28  5051.2 2055.55  5084.4 2057.01  5095.9 2058.18
  5141.5 2060.26  5158.8 2059.02  5164.3 2059.72  5204.4 2059.84  5227.2 2060.75
    5250 2060.54  5255.6 2059.78  5360.6 2060.62  5654.3 2061.29  5886.9 2062.96
#Mann= 6 ,-1 , 0
  4299.2     .16       0  4397.7     .07       0  4743.5     .16       0
  4766.1     .07       0  5019.9     .07       0    5024     .07       0
Bank Sta=5019.9,5024
XS Rating Curve= 0 ,0
Exp/Cntr=0.3,0.1

Type RM Length L Ch R = 1 ,1881    ,177,177,177
BEGIN DESCRIPTION:
Bluff Creek Trib2T 3.0
END DESCRIPTION:
XS GIS Cut Line= 3
      1409232.47      6890528.45      1408487.83      6890820.88
      1408245.25      6891579.01
#Sta/Elev= 30
    4200 2078.06  4231.9 2077.05  4321.4  2072.4  4326.7 2073.43  4358.4 2070.54
  4385.8 2070.09  4422.9 2069.28  4435.2 2067.89  4513.8 2064.69  4519.6 2063.79
  4543.6 2063.84  4646.6 2060.89  4820.4 2058.98  4906.4 2056.97  4938.6 2055.13
  4952.9 2053.17  4960.1 2050.94  4977.3  2048.1  4982.7 2048.56  4996.8 2044.58
    4997 2044.08  5000.9 2044.58  5024.5 2050.73  5029.7 2053.27  5061.9 2055.12
  5142.2 2057.26  5201.9 2058.11  5388.7 2059.21    5592 2059.01    5796 2059.68
#Mann= 8 ,-1 , 0
    4200     .07       0  4231.9    .035       0  4385.8     .07       0
  4996.8     .07       0  5000.9     .07       0  5142.2     .16       0
  5201.9     .07       0    5592    .035       0
Bank Sta=4996.8,5000.9
XS Rating Curve= 0 ,0
Exp/Cntr=0.3,0.1

Type RM Length L Ch R = 1 ,1704    ,264,264,264
BEGIN DESCRIPTION:
Bluff Creek Trib2T 4129
END DESCRIPTION:
XS GIS Cut Line= 3
      1408708.51      6890700.89      1408363.96      6890694.67
      1408266.51      6890914.54
#Sta/Elev= 30
  4655.4 2059.67  4698.9 2059.28  4728.9 2058.32  4788.9 2057.79  4818.9 2056.84
  4838.9 2055.26  4888.9 2053.06  4898.9  2052.7  4908.9 2053.18    4939 2051.59
    4959 2052.68  4963.3 2052.33    4997 2049.62  5009.4 2049.64  5025.5 2048.72
  5030.7 2041.04  5030.9 2040.54  5034.5 2040.54  5034.8 2041.04  5038.2 2044.18
  5047.4  2047.9    5056 2050.39  5091.1 2055.63  5113.5 2056.36    5124 2056.09
  5131.3  2056.8  5154.6 2056.55  5177.9 2057.26  5189.6 2056.84  5240.5 2056.92
#Mann= 4 ,-1 , 0
  4655.4     .07       0  4963.3     .16       0  5030.7     .07       0
  5034.8     .16       0
Bank Sta=5030.7,5034.8
XS Rating Curve= 0 ,0
Exp/Cntr=0.3,0.1

Type RM Length L Ch R = 1 ,1440    ,293,293,293
BEGIN DESCRIPTION:
Bluff Creek Trib2T 4128
END DESCRIPTION:
XS GIS Cut Line= 3
      1408868.19      6890476.93      1408496.01      6890480.99
      1408225.19      6890663.71
#Sta/Elev= 30
  4627.8 2062.33    4661  2061.7    4681 2062.07    4691 2061.07    4801 2058.22
    4831  2056.9    4871 2056.43  4899.2  2055.1    4911  2054.9    4931 2052.89
    4951  2047.9    4971  2046.1    4991  2046.6    4998 2047.93  5018.3 2039.66
  5018.6 2039.16  5022.2 2039.16  5022.5 2039.66  5026.4 2040.05  5030.4 2043.02
  5035.4 2046.74  5041.4 2047.03  5056.4 2049.76  5071.3 2051.25  5077.4  2051.1
  5085.7 2052.19  5107.3 2053.23  5161.8 2054.75  5277.1 2056.41  5326.7 2056.69
#Mann= 7 ,-1 , 0
  4627.8     .07       0  4899.2     .16       0  5018.3     .07       0
  5022.5     .16       0  5030.4     .07       0  5161.8     .16       0
  5277.1     .07       0
#XS Ineff= 2 , 0
         4996.35 2052.28
Permanent Ineff=
       F       F
Bank Sta=5018.3,5022.5
XS Rating Curve= 0 ,0
Exp/Cntr=0.3,0.1

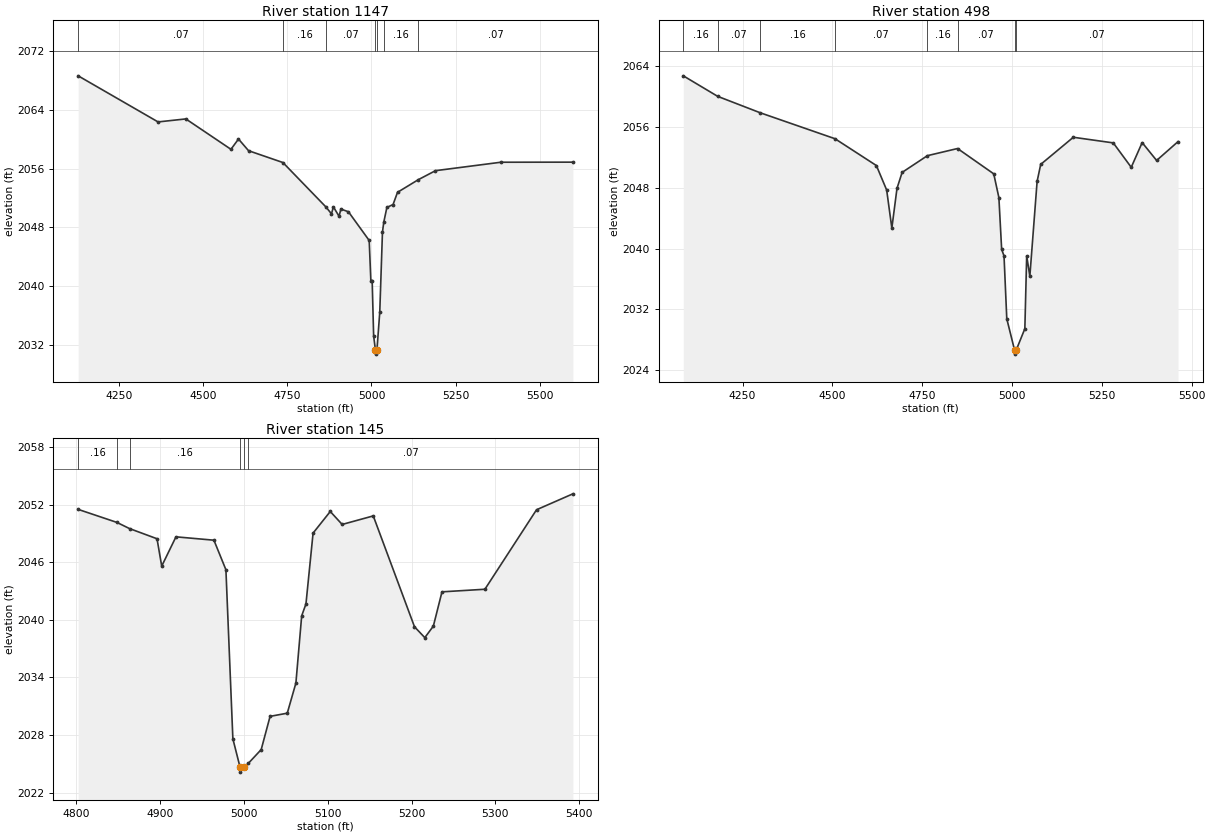
Type RM Length L Ch R = 1 ,1147    ,649,649,649
BEGIN DESCRIPTION:
Bluff Creek Trib2T 2.0
END DESCRIPTION:
XS GIS Cut Line= 3
      1409051.35      6889916.76      1408271.29      6890304.71
       1408080.4      6890871.63
#Sta/Elev= 30
  4128.8 2068.66  4366.1 2062.38  4448.6 2062.79  4582.6 2058.65    4605 2060.05
  4634.9 2058.46  4736.9 2056.85  4864.6  2050.8  4881.2 2049.86  4886.8 2050.82
  4903.6 2049.53  4909.2 2050.51  4931.6 2050.14  4993.2 2046.23  4998.1 2040.77
    5002 2040.77  5006.4 2033.22  5011.9 2031.25  5012.2 2030.75  5016.1 2031.25
  5024.6 2036.47  5032.6 2047.38  5036.5 2048.72  5045.7 2050.73  5064.1 2051.13
  5077.3 2052.79  5138.9 2054.51  5190.1 2055.74  5384.3 2056.89  5598.2  2056.9
#Mann= 7 ,-1 , 0
  4128.8     .07       0  4736.9     .16       0  4864.6     .07       0
  5011.9     .07       0  5016.1     .07       0  5036.5     .16       0
  5138.9     .07       0
Bank Sta=5011.9,5016.1
XS Rating Curve= 0 ,0
Exp/Cntr=0.3,0.1

Type RM Length L Ch R = 1 ,498     ,353,353,353
BEGIN DESCRIPTION:
Bluff Creek Trib2T 1.0
END DESCRIPTION:
XS GIS Cut Line= 3
      1408625.34      6889420.59      1407924.63      6890008.68
       1407866.9      6890467.26
#Sta/Elev= 30
  4085.2 2062.72  4180.9 2060.02  4299.3 2057.86  4507.3 2054.45  4622.6 2050.92
  4651.2  2047.7  4665.6 2042.69  4679.9 2047.91  4694.2 2050.02  4764.6 2052.22
  4848.5 2053.16  4949.2 2049.83  4963.5 2046.71  4971.2  2039.9  4977.8 2039.04
  4985.5 2030.77  5007.3 2026.62  5007.5 2026.12  5011.5 2026.62  5035.8 2029.47
  5040.9 2039.05  5049.7 2036.37  5069.9 2048.83  5079.9 2051.07  5170.7 2054.64
  5281.9  2053.9  5331.9 2050.69  5362.3 2053.94  5402.5 2051.59  5462.2 2054.07
#Mann= 8 ,-1 , 0
  4085.2     .16       0  4180.9     .07       0  4299.3     .16       0
  4507.3     .07       0  4764.6     .16       0  4848.5     .07       0
  5007.3     .07       0  5011.5     .07       0
Bank Sta=5007.3,5011.5
XS Rating Curve= 0 ,0
Exp/Cntr=0.3,0.1

Type RM Length L Ch R = 1 ,145     ,0,0,0
BEGIN DESCRIPTION:
Bluff Creek Trib2T 4130
END DESCRIPTION:
XS GIS Cut Line= 3
      1407953.75      6889621.59       1407775.6      6889707.55
      1407688.96      6890090.37
#Sta/Elev= 30
  4802.2  2051.5  4848.5 2050.14  4863.5  2049.5  4896.3 2048.44  4901.9 2045.59
  4918.9 2048.64  4964.2 2048.29  4978.5 2045.21  4986.8  2027.6  4995.4 2024.63
  4995.7 2024.13  4999.8 2024.63  5005.1 2025.03  5020.6 2026.48  5031.2 2029.94
  5051.7 2030.27    5062 2033.41  5068.9 2040.41    5074 2041.65  5082.5 2049.03
    5103 2051.28  5117.2 2049.93  5154.3 2050.82  5203.5 2039.27  5215.8 2038.14
    5226 2039.34  5236.3 2042.91  5287.5 2043.18  5349.1 2051.46  5392.5 2053.12
#Mann= 6 ,-1 , 0
  4802.2     .16       0  4848.5     .07       0  4863.5     .16       0
  4995.4     .07       0  4999.8     .07       0  5005.1     .07       0
Bank Sta=4995.4,4999.8
XS Rating Curve= 0 ,0
Exp/Cntr=0.3,0.1

Chan Stop Cuts=-1
Use User Specified Reach Order=0
Composite Channel Slope=5