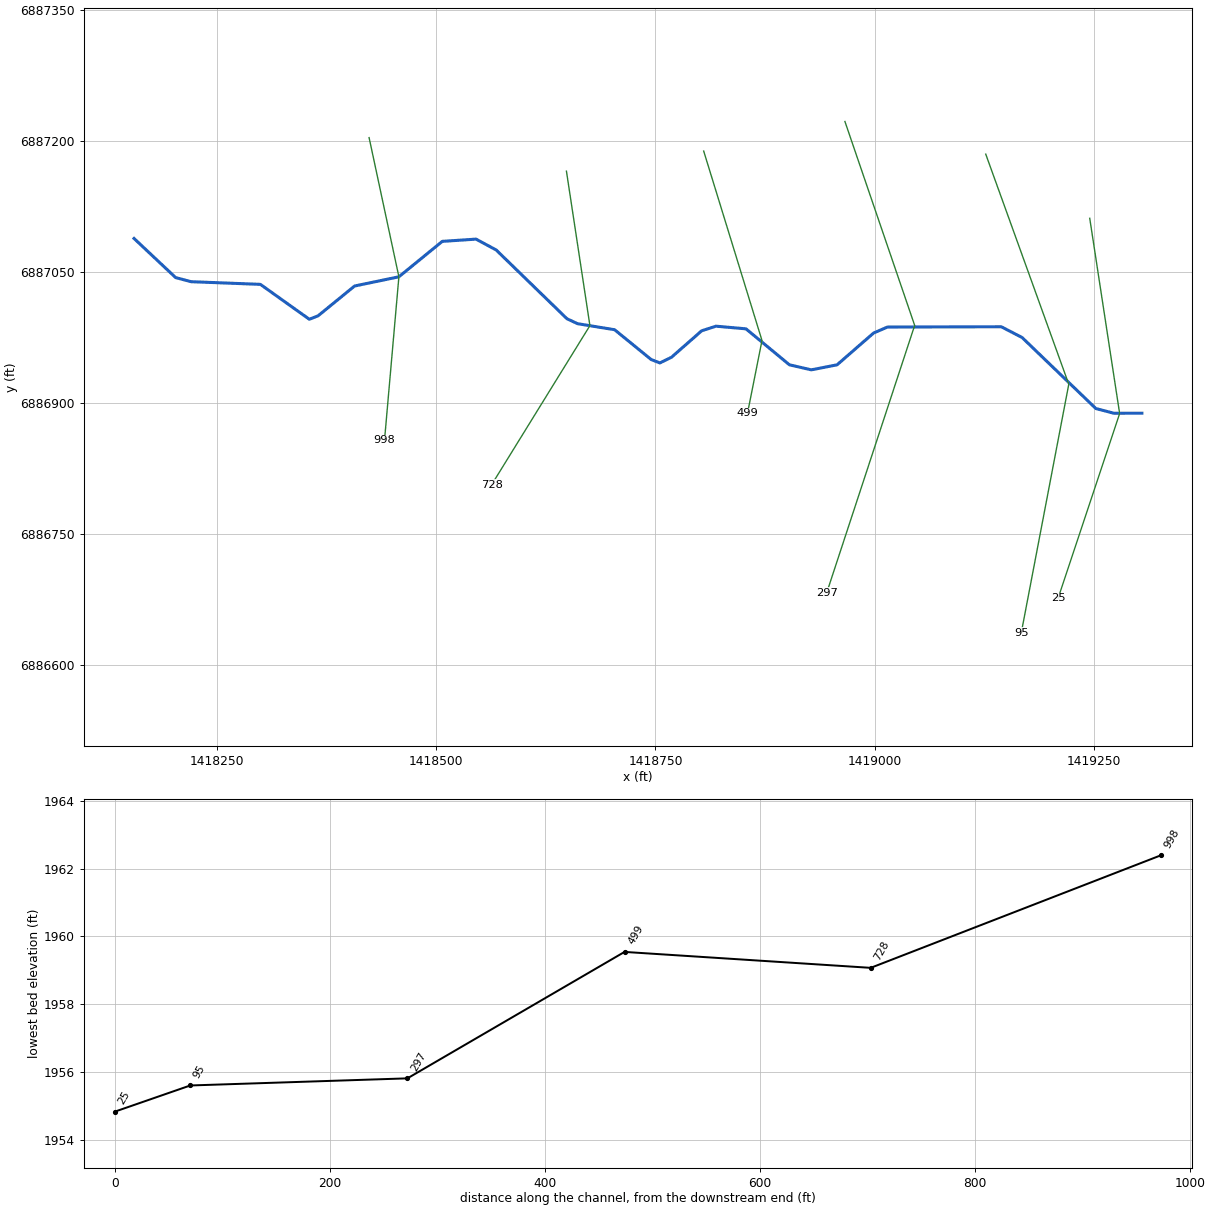
--- Cottonwood Creek Trib.prj (project) ---

Proj Title=Cottonwood Creek Trib Base Level Engineering
Current Plan=p01
Default Exp/Contr=0.3,0.1
English Units
Geom File=g01
Flow File=f01
Plan File=p01
Y Axis Title=Elevation
X Axis Title(PF)=Main Channel Distance
X Axis Title(XS)=Station
BEGIN DESCRIPTION:
Cottonwood Creek Trib
END DESCRIPTION:
DSS Export Rating Curves= 0
DSS Export Rating Curve Sorted= 0
DSS Export Volume Flow Curves= 0
DXF OffsetX= 0
DXF OffsetY= 0
DXF ScaleX= 1
DXF ScaleY= 10

--- Cottonwood Creek Trib.p01 (plan) ---

Plan Title=Multiple Run
Short Identifier=Multiple
Geom File=g01
Flow File=f01
Subcritical Flow
K Sum by GR= 0
Std Step Tol= 0.01
Critical Tol= 0.01
Num of Std Step Trials= 20
Max Error Tol= 0.3
Flow Tol Ratio= 0.001
Split Flow NTrial= 30
Split Flow Tol= 0.02
Split Flow Ratio= 0.02
Log Output Level= 0
Friction Slope Method= 1
Unsteady Friction Slope Method= 2
Unsteady Bridges Friction Slope Method= 1
Parabolic Critical Depth
Global Vel Dist=  1 , 1 , 1
Global Log Level= 0
CheckData=True
Encroach Param= -1, 0, 0, 0
BEGIN DESCRIPTION:
Multiple Run
END DESCRIPTION:

--- Cottonwood Creek Trib.f01 (steady flow) ---

Flow Title=Multiple
Program Version=4.10
Number of Profiles= 7
Profile Names=10-year,25-year,50-year,1pct_min,100-year,1pct_plu,500-year
River Rch & RM=Cottonwood Creek,Reach-1         ,998
     377     552     703     447     893    1781    1454
Boundary for River Rch & Prof#=Cottonwood Creek,Reach-1         , 1
Up Type= 0
Dn Type= 3
Dn Slope=0.005
Boundary for River Rch & Prof#=Cottonwood Creek,Reach-1         , 2
Up Type= 0
Dn Type= 3
Dn Slope=0.005
Boundary for River Rch & Prof#=Cottonwood Creek,Reach-1         , 3
Up Type= 0
Dn Type= 3
Dn Slope=0.005
Boundary for River Rch & Prof#=Cottonwood Creek,Reach-1         , 4
Up Type= 0
Dn Type= 3
Dn Slope=0.005
Boundary for River Rch & Prof#=Cottonwood Creek,Reach-1         , 5
Up Type= 0
Dn Type= 3
Dn Slope=0.005
Boundary for River Rch & Prof#=Cottonwood Creek,Reach-1         , 6
Up Type= 0
Dn Type= 3
Dn Slope=0.005
Boundary for River Rch & Prof#=Cottonwood Creek,Reach-1         , 7
Up Type= 0
Dn Type= 3
Dn Slope=0.005
DSS Import GetInterval= 0
DSS Import GetPeak= 0
DSS Import FillOption= 0

--- Cottonwood Creek Trib.g01 (geometry) ---

Geom Title=Existing Conditions

River Reach=Cottonwood Creek,Reach-1
Reach XY= 30
      1418155.00      6887088.00      1418202.45      6887043.22
      1418220.22      6887038.52      1418299.12      6887035.48
      1418355.01      6886995.53      1418364.93      6886999.42
      1418406.64      6887033.58      1418457.19      6887044.13
      1418506.73      6887084.69      1418545.22      6887087.25
      1418568.20      6887074.85      1418648.96      6886996.14
      1418661.05      6886990.47      1418703.35      6886983.55
      1418745.08      6886949.43      1418755.00      6886945.56
      1418768.23      6886952.01      1418802.71      6886982.35
      1418819.04      6886987.61      1418853.26      6886984.57
      1418902.80      6886943.41      1418927.80      6886937.63
      1418957.18      6886943.38      1418998.93      6886979.82
      1419014.66      6886986.61      1419144.56      6886986.96
      1419168.32      6886974.63      1419252.49      6886893.33
      1419273.12      6886887.93      1419305.00      6886888.00

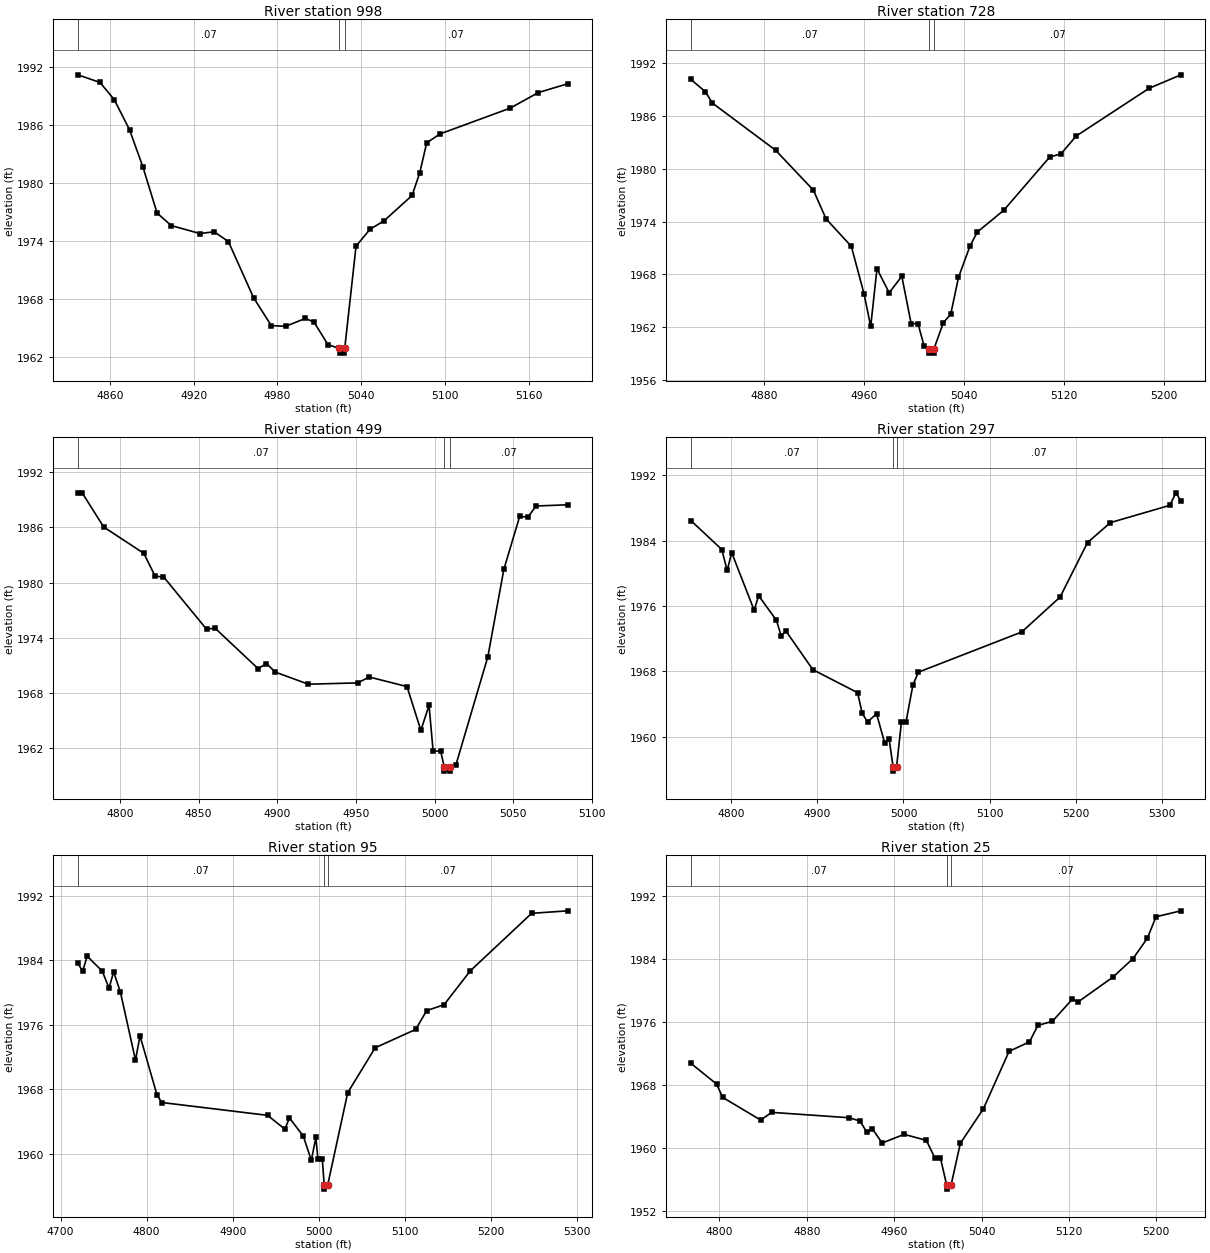
Type RM Length L Ch R = 1,998,270,270,270
BEGIN DESCRIPTION:
Cottonwood Creek Trib 5.0
END DESCRIPTION:
XS GIS Cut Line= 3
      1418423.19      6887203.44      1418457.19      6887044.13
      1418440.77      6886856.85
#Sta/Elev= 30
  4837.1 1991.22  4852.9 1990.43  4863.1 1988.66  4874.1 1985.52  4883.6 1981.70
  4893.8 1976.90  4904.0 1975.60  4924.5 1974.78  4934.7 1974.96  4944.9 1973.94
  4962.9 1968.13  4975.6 1965.24  4985.8 1965.17  5000.0 1965.98  5006.2 1965.61
  5016.2 1963.26  5024.2 1962.89  5024.5 1962.39  5028.0 1962.39  5028.2 1962.89
  5036.3 1973.48  5046.3 1975.22  5056.3 1976.09  5076.4 1978.72  5081.9 1981.06
  5086.9 1984.18  5096.5 1985.10  5146.7 1987.77  5166.8 1989.38  5188.0 1990.30
#Mann=3,-1,0
  4837.1    0.07       0  5024.2    0.07       0  5028.2    0.07       0
Bank Sta=5024.2,5028.2
Exp/Cntr=0.3,0.1

Type RM Length L Ch R = 1,728,229,229,229
BEGIN DESCRIPTION:
Cottonwood Creek Trib 4.0
END DESCRIPTION:
XS GIS Cut Line= 3
      1418648.38      6887165.03      1418675.16      6886988.24
      1418563.11      6886806.28
#Sta/Elev= 30
  4821.2 1990.14  4832.7 1988.76  4838.4 1987.46  4889.0 1982.11  4919.3 1977.57
  4929.4 1974.32  4949.7 1971.19  4959.8 1965.83  4965.2 1962.10  4970.2 1968.65
  4980.0 1965.92  4990.1 1967.80  4997.6 1962.42  5003.1 1962.42  5008.0 1959.85
  5011.9 1959.57  5012.1 1959.07  5015.6 1959.07  5015.9 1959.57  5023.4 1962.53
  5029.3 1963.48  5035.5 1967.66  5044.7 1971.22  5050.6 1972.82  5071.8 1975.29
  5108.5 1981.32  5117.7 1981.71  5129.8 1983.72  5188.2 1989.14  5213.7 1990.67
#Mann=3,-1,0
  4821.2    0.07       0  5011.9    0.07       0  5015.9    0.07       0
Bank Sta=5011.9,5015.9
Exp/Cntr=0.3,0.1

Type RM Length L Ch R = 1,499,202,202,202
BEGIN DESCRIPTION:
Cottonwood Creek Trib 3.0
END DESCRIPTION:
XS GIS Cut Line= 3
      1418804.99      6887188.05      1418871.52      6886971.22
      1418855.01      6886888.04
#Sta/Elev= 30
  4773.2 1989.76  4775.9 1989.76  4789.6 1986.05  4815.1 1983.19  4822.4 1980.68
  4827.6 1980.65  4855.1 1974.93  4860.3 1975.08  4887.8 1970.67  4893.1 1971.22
  4898.8 1970.29  4919.7 1968.98  4951.1 1969.12  4958.5 1969.76  4982.5 1968.72
  4991.3 1963.97  4996.5 1966.68  4999.1 1961.72  5003.9 1961.72  5006.1 1960.04
  5006.3 1959.54  5009.8 1959.54  5010.1 1960.04  5013.5 1960.16  5033.9 1971.96
  5044.1 1981.46  5054.2 1987.23  5059.3 1987.09  5064.5 1988.33  5084.8 1988.46
#Mann=3,-1,0
  4773.2    0.07       0  5006.1    0.07       0  5010.1    0.07       0
Bank Sta=5006.1,5010.1
Exp/Cntr=0.3,0.1

Type RM Length L Ch R = 1,297,202,202,202
BEGIN DESCRIPTION:
Cottonwood Creek Trib 2.0
END DESCRIPTION:
XS GIS Cut Line= 3
      1418966.15      6887221.90      1419045.74      6886988.50
      1418945.40      6886682.53
#Sta/Elev= 30
  4753.4 1986.43  4789.2 1982.90  4795.4 1980.34  4800.7 1982.51  4826.7 1975.49
  4832.0 1977.25  4852.6 1974.25  4858.1 1972.32  4863.4 1972.97  4894.9 1968.21
  4946.8 1965.40  4952.1 1962.89  4958.3 1961.82  4968.8 1962.82  4978.2 1959.26
  4983.4 1959.71  4988.0 1956.31  4988.2 1955.81  4992.0 1956.31  4997.6 1961.78
  5002.9 1961.78  5011.0 1966.35  5017.4 1967.91  5137.3 1972.82  5181.8 1977.09
  5213.6 1983.75  5240.2 1986.19  5309.1 1988.30  5316.2 1989.83  5322.0 1988.84
#Mann=3,-1,0
  4753.4    0.07       0  4988.0    0.07       0  4992.0    0.07       0
Bank Sta=4988,4992
Exp/Cntr=0.3,0.1

Type RM Length L Ch R = 1,95,70,70,70
BEGIN DESCRIPTION:
Cottonwood Creek Trib 1.0
END DESCRIPTION:
XS GIS Cut Line= 3
      1419126.84      6887184.52      1419221.59      6886921.15
      1419167.39      6886636.67
#Sta/Elev= 30
  4720.1 1983.60  4725.6 1982.63  4730.9 1984.48  4748.3 1982.64  4756.3 1980.54
  4761.6 1982.53  4769.5 1980.03  4787.0 1971.60  4792.3 1974.60  4812.1 1967.25
  4817.7 1966.34  4940.6 1964.75  4960.6 1963.04  4966.0 1964.42  4982.1 1962.17
  4991.4 1959.17  4996.7 1962.01  4999.0 1959.39  5004.1 1959.39  5006.4 1956.10
  5006.6 1955.60  5010.4 1956.10  5033.7 1967.56  5065.6 1973.13  5112.7 1975.40
  5125.4 1977.73  5145.7 1978.47  5176.3 1982.68  5247.5 1989.80  5289.6 1990.11
#Mann=3,-1,0
  4720.1    0.07       0  5006.4    0.07       0  5010.4    0.07       0
Bank Sta=5006.4,5010.4
Exp/Cntr=0.3,0.1

Type RM Length L Ch R = 1,25,0,0,0
BEGIN DESCRIPTION:
Cottonwood Creek Trib 4316
END DESCRIPTION:
XS GIS Cut Line= 3
      1419245.50      6887111.11      1419279.63      6886887.60
      1419209.46      6886676.35
#Sta/Elev= 30
  4773.9 1970.75  4797.3 1968.14  4803.0 1966.44  4837.7 1963.58  4847.9 1964.55
  4918.7 1963.87  4928.8 1963.45  4935.0 1962.01  4940.1 1962.45  4949.0 1960.67
  4969.2 1961.77  4989.5 1961.00  4997.3 1958.77  5002.4 1958.77  5008.1 1955.33
  5008.4 1954.83  5012.1 1955.33  5020.6 1960.63  5041.7 1965.00  5065.2 1972.27
  5083.9 1973.48  5091.6 1975.56  5104.9 1976.08  5123.2 1978.89  5128.5 1978.54
  5160.2 1981.66  5178.7 1984.02  5191.8 1986.58  5199.8 1989.32  5222.6 1990.07
#Mann=3,-1,0
  4773.9    0.07       0  5008.1    0.07       0  5012.1    0.07       0
Bank Sta=5008.1,5012.1
Exp/Cntr=0.3,0.1

Chan Stop Cuts=-1