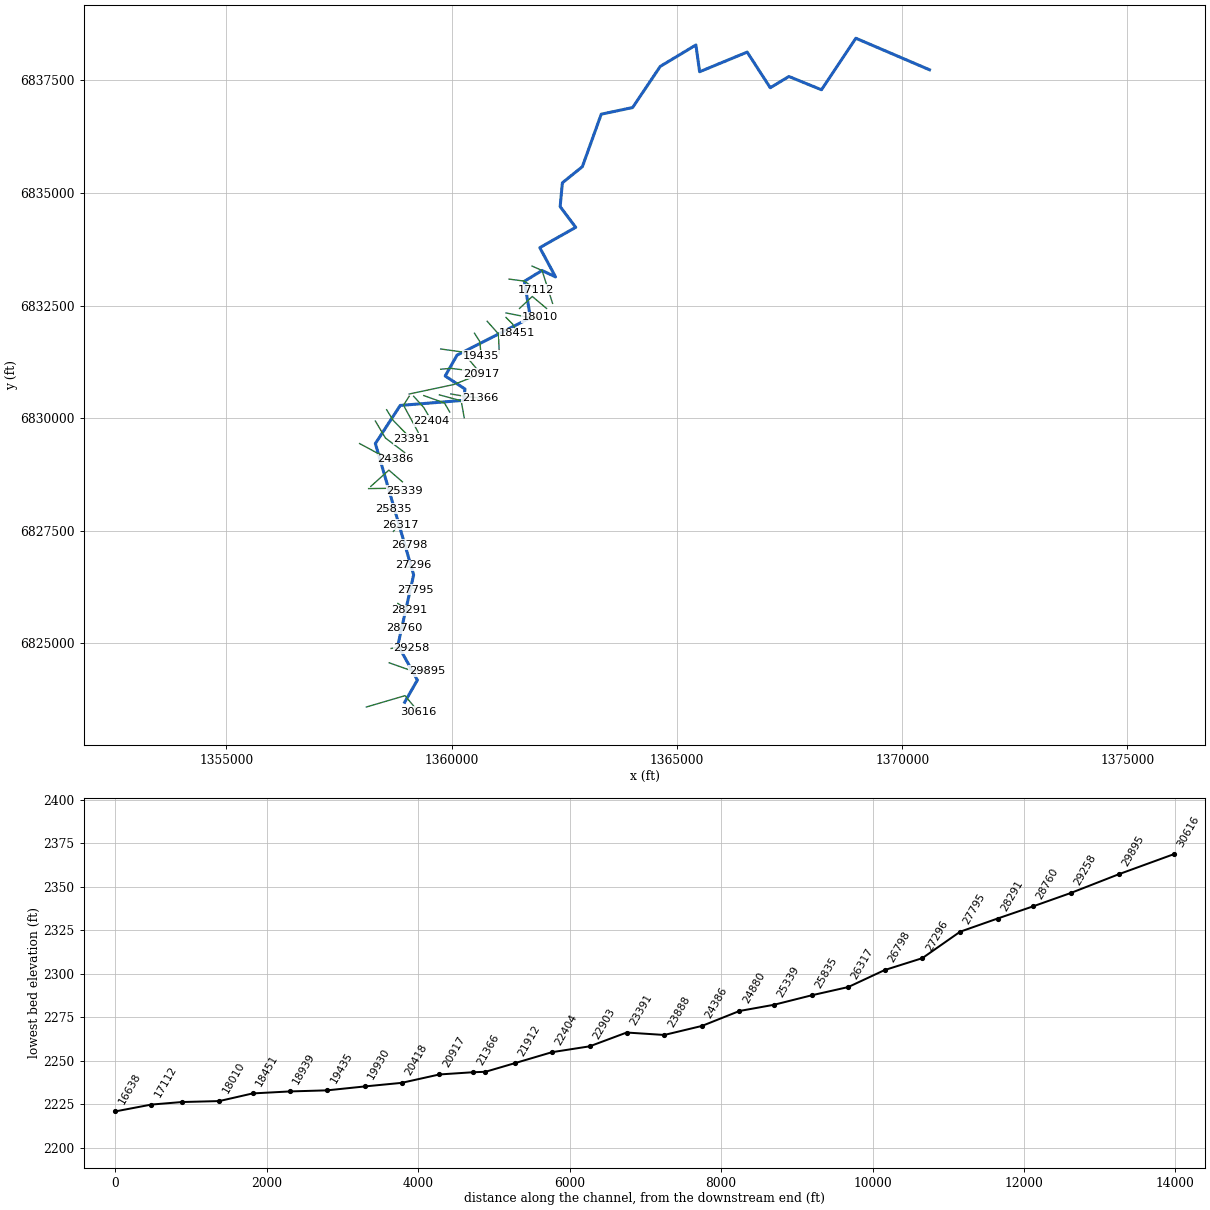
--- Finn Creek.prj (project) ---

Proj Title=Finn Creek Base Level Engineering
Current Plan=p01
Default Exp/Contr=0.3,0.1
English Units
Geom File=g01
Flow File=f01
Plan File=p01
Y Axis Title=Elevation
X Axis Title(PF)=Main Channel Distance
X Axis Title(XS)=Station
BEGIN DESCRIPTION:
Finn Creek
END DESCRIPTION:
DSS Export Rating Curves= 0
DSS Export Rating Curve Sorted= 0
DSS Export Volume Flow Curves= 0
DXF OffsetX= 0
DXF OffsetY= 0
DXF ScaleX= 1
DXF ScaleY= 10

--- Finn Creek.p01 (plan) ---

Plan Title=Multiple Run
Short Identifier=Multiple
Geom File=g01
Flow File=f01
Subcritical Flow
K Sum by GR= 0
Std Step Tol= 0.01
Critical Tol= 0.01
Num of Std Step Trials= 20
Max Error Tol= 0.3
Flow Tol Ratio= 0.001
Split Flow NTrial= 30
Split Flow Tol= 0.02
Split Flow Ratio= 0.02
Log Output Level= 0
Friction Slope Method= 1
Unsteady Friction Slope Method= 2
Unsteady Bridges Friction Slope Method= 1
Parabolic Critical Depth
Global Vel Dist=  1 , 1 , 1
Global Log Level= 0
CheckData=True
Encroach Param= -1, 0, 0, 0
BEGIN DESCRIPTION:
Multiple Run
END DESCRIPTION:

--- Finn Creek.f01 (steady flow) ---

Flow Title=Multiple
Program Version=4.10
Number of Profiles= 7
Profile Names=10-year,25-year,50-year,1pct_min,100-year,1pct_plu,500-year
River Rch & RM=Finn Creek,Reach-1         ,30616
     309     446     563     354     706    1409    1126
River Rch & RM=Finn Creek,Reach-1         ,26317
     317     461     585     370     738    1472    1187
River Rch & RM=Finn Creek,Reach-1         ,24386
    1047    1593    2082    1347    2688    5363    4550
River Rch & RM=Finn Creek,Reach-1         ,21366
    1091    1661    2172    1407    2807    5601    4758
River Rch & RM=Finn Creek,Reach-1         ,20418
    1178    1799    2359    1531    3056    6097    5203
River Rch & RM=Finn Creek,Reach-1         ,19435
    1224    1874    2460    1598    3189    6363    5441
River Rch & RM=Finn Creek,Reach-1         ,16033
    1234    1887    2477    1609    3210    6404    5472
River Rch & RM=Finn Creek,Reach-1         ,15388
    1320    2025    2662    1732    3455    6894    5909
River Rch & RM=Finn Creek,Reach-1         ,14273
    1335    2045    2685    1744    3480    6944    5936
River Rch & RM=Finn Creek,Reach-1         ,9540
    1447    2217    2912    1892    3774    7531    6437
Boundary for River Rch & Prof#=Finn Creek,Reach-1         , 1
Up Type= 0
Dn Type= 3
Dn Slope=0.005
Boundary for River Rch & Prof#=Finn Creek,Reach-1         , 2
Up Type= 0
Dn Type= 3
Dn Slope=0.005
Boundary for River Rch & Prof#=Finn Creek,Reach-1         , 3
Up Type= 0
Dn Type= 3
Dn Slope=0.005
Boundary for River Rch & Prof#=Finn Creek,Reach-1         , 4
Up Type= 0
Dn Type= 3
Dn Slope=0.005
Boundary for River Rch & Prof#=Finn Creek,Reach-1         , 5
Up Type= 0
Dn Type= 3
Dn Slope=0.005
Boundary for River Rch & Prof#=Finn Creek,Reach-1         , 6
Up Type= 0
Dn Type= 3
Dn Slope=0.005
Boundary for River Rch & Prof#=Finn Creek,Reach-1         , 7
Up Type= 0
Dn Type= 3
Dn Slope=0.005
DSS Import GetInterval= 0
DSS Import GetPeak= 0
DSS Import FillOption= 0

--- Finn Creek.g01 (geometry) ---

Geom Title=Existing Conditions
Program Version=4.10

River Reach=Finn Creek      ,Reach-1
Reach XY= 30
      1358955.36      6823694.14      1359237.04      6824186.33
      1358804.77      6824962.93      1359154.48      6826522.78
        1358305.        6829438.      1358856.52      6830284.27
      1360264.98      6830398.05      1360294.66      6830648.13
        1359855.        6830938.      1360118.49      6831401.56
      1361747.32      6832231.48      1361612.59      6833041.35
       1362005.3       6833280.8        1362305.        6833138.
        1361955.        6833788.      1362751.98      6834239.39
      1362406.96      6834699.97      1362456.09      6835227.45
      1362899.48      6835585.57      1363318.62      6836751.21
      1364014.97       6836898.7      1364628.11      6837811.74
      1365420.48      6838288.01       1365502.3      6837693.36
      1366558.32      6838129.96      1367070.22      6837338.52
      1367484.73      6837588.41      1368207.44      6837293.39
      1368970.15      6838437.62        1370605.        6837738.

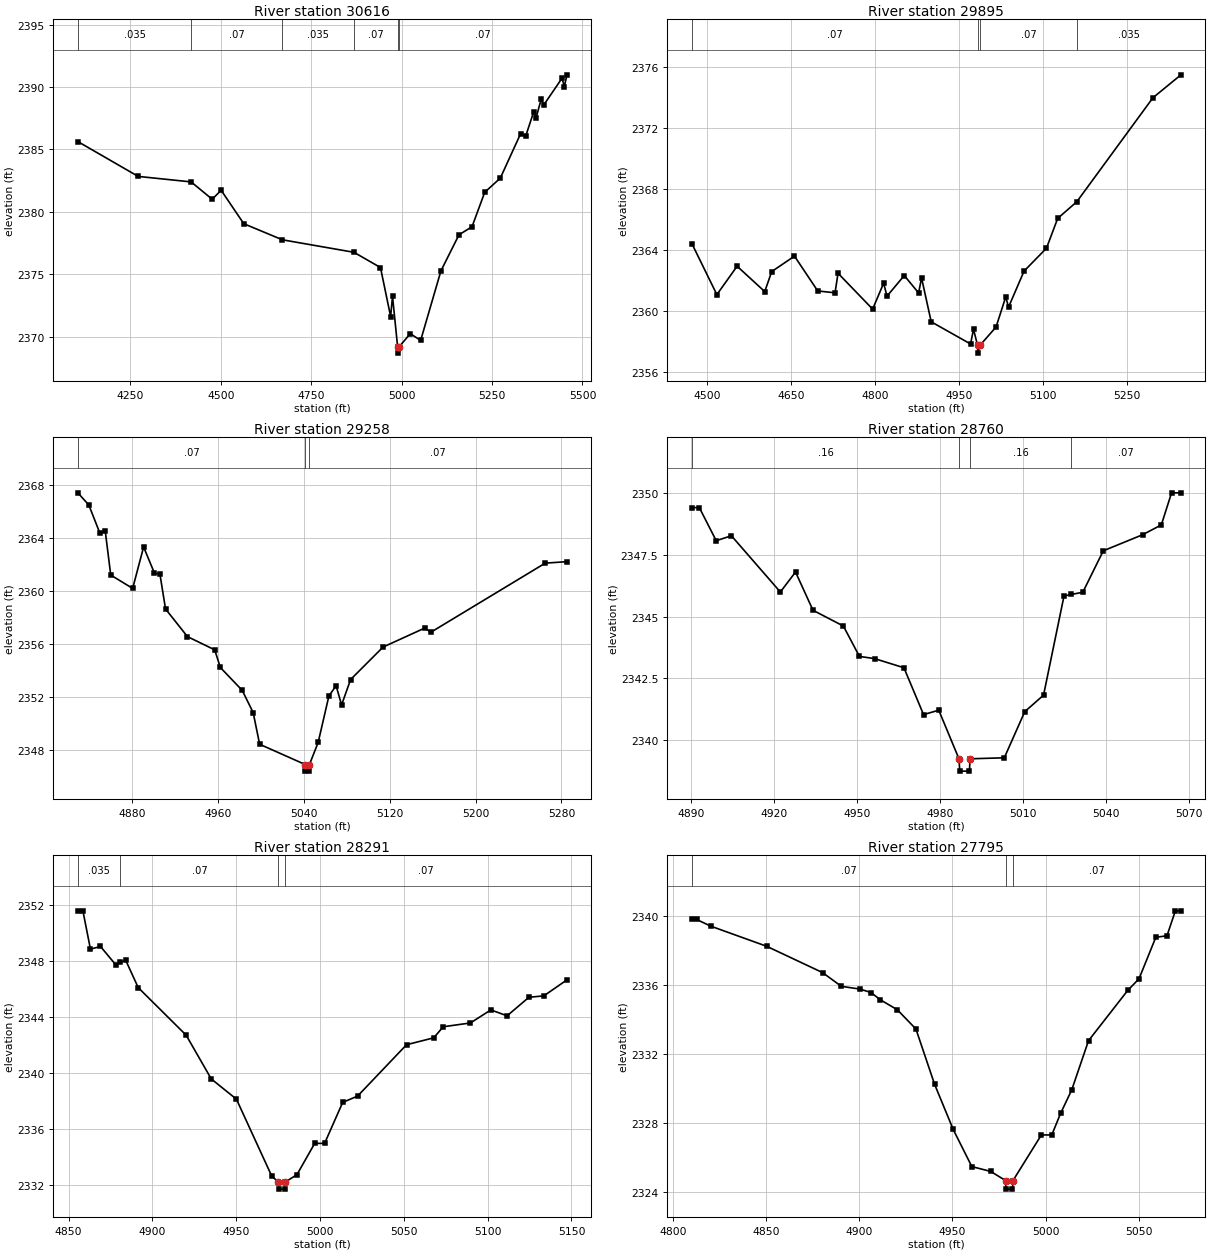
Type RM Length L Ch R = 1 ,30616   ,721,721,721
BEGIN DESCRIPTION:
Finn Creek 52.0
END DESCRIPTION:
XS GIS Cut Line= 3
      1358104.97      6823587.99       1358963.6      6823840.19
      1359254.99      6823488.01
#Sta/Elev= 30
  4105.1 2385.63  4271.9 2382.84  4418.2  2382.4  4476.4 2381.01  4501.2 2381.73
  4563.7 2379.05  4670.6 2377.76  4868.2 2376.76  4941.6 2375.54  4969.7 2371.61
  4974.9 2373.24    4989 2369.18  4989.3 2368.68    4993 2369.18    5024 2370.24
  5052.7  2369.7  5108.7 2375.27  5158.6 2378.16  5194.7 2378.81  5229.8 2381.57
  5272.8  2382.7  5328.8 2386.25  5343.1 2386.07  5365.3 2388.03  5371.8 2387.54
  5386.1 2389.05  5392.6 2388.55  5443.5 2390.71  5449.9 2390.04  5457.1 2390.98
#Mann= 6 ,-1 , 0
  4105.1    .035       0  4418.2     .07       0  4670.6    .035       0
  4868.2     .07       0    4989     .07       0    4993     .07       0
Bank Sta=4989,4993
XS Rating Curve= 0 ,0
Exp/Cntr=0.3,0.1

Type RM Length L Ch R = 1 ,29895   ,637,637,637
BEGIN DESCRIPTION:
Finn Creek 51.0
END DESCRIPTION:
XS GIS Cut Line= 3
      1358612.42      6824569.44        1359109.      6824393.57
      1359454.96        6824388.
#Sta/Elev= 30
  4473.2 2364.42  4517.8 2361.08  4553.9 2362.94  4603.2 2361.28  4615.7 2362.59
  4656.3  2363.6  4697.8 2361.32  4728.7  2361.2    4734 2362.48  4795.8 2360.13
  4815.4 2361.83  4821.4 2360.98  4852.2 2362.33  4877.8 2361.19  4883.1 2362.17
  4900.3  2359.3  4970.5 2357.85  4975.8 2358.81  4983.1 2357.75  4983.4 2357.25
  4987.1 2357.75    5016 2358.96  5033.3 2360.93  5038.3 2360.26    5066 2362.62
    5106 2364.12    5126 2366.07  5160.1 2367.16    5296 2373.97    5346 2375.47
#Mann= 4 ,-1 , 0
  4473.2     .07       0  4983.1     .07       0  4987.1     .07       0
  5160.1    .035       0
Bank Sta=4983.1,4987.1
XS Rating Curve= 0 ,0
Exp/Cntr=0.3,0.1

Type RM Length L Ch R = 1 ,29258   ,498,498,498
BEGIN DESCRIPTION:
Finn Creek 50.0
END DESCRIPTION:
XS GIS Cut Line= 3
        1358655.        6824888.      1358821.89      6824921.43
      1359105.02        6824888.
#Sta/Elev= 30
  4829.8 2367.44    4840 2366.52  4850.2 2364.41  4855.3 2364.54  4860.4 2361.23
  4880.8 2360.22    4891 2363.35  4901.1 2361.37  4906.2  2361.3  4911.4 2358.67
  4931.8 2356.58  4957.2 2355.58  4962.4 2354.25  4982.8 2352.52    4993 2350.84
    4999 2348.45  5041.4 2346.92  5041.7 2346.42  5045.2 2346.42  5045.4 2346.92
  5053.5 2348.59  5063.5  2352.1  5070.2 2352.87  5075.3 2351.42  5083.7 2353.34
  5113.9 2355.79  5153.1 2357.24  5158.2  2356.9  5264.9 2362.13  5285.1 2362.24
#Mann= 3 ,-1 , 0
  4829.8     .07       0  5041.4     .07       0  5045.4     .07       0
Bank Sta=5041.4,5045.4
XS Rating Curve= 0 ,0
Exp/Cntr=0.3,0.1

Type RM Length L Ch R = 1 ,28760   ,469,469,469
BEGIN DESCRIPTION:
Finn Creek 49.0
END DESCRIPTION:
XS GIS Cut Line= 3
      1358805.03      6825338.01      1358905.09      6825382.96
      1358955.02      6825337.98
#Sta/Elev= 28
  4890.3 2349.42    4893 2349.42  4899.1 2348.08  4904.6 2348.28  4922.3    2346
  4927.8 2346.81  4934.1 2345.26  4945.1 2344.62  4950.9 2343.39  4956.4  2343.3
    4967 2342.93  4974.1 2341.03  4979.6 2341.21  4986.9 2339.24  4987.2 2338.74
  4990.7 2338.74  4990.9 2339.24  5003.3 2339.28  5010.7 2341.15  5017.5 2341.82
  5024.9 2345.84  5027.5  2345.9  5031.7 2345.99  5039.1 2347.67  5053.3 2348.32
  5060.1 2348.72  5063.8 2350.02  5067.2 2350.02
#Mann= 4 ,-1 , 0
  4890.3     .16       0  4986.9     .07       0  4990.9     .16       0
  5027.5     .07       0
Bank Sta=4986.9,4990.9
XS Rating Curve= 0 ,0
Exp/Cntr=0.3,0.1

Type RM Length L Ch R = 1 ,28291   ,496,496,496
BEGIN DESCRIPTION:
Finn Creek 48.0
END DESCRIPTION:
XS GIS Cut Line= 3
      1358805.04      6825887.97      1358925.31      6825807.87
      1359054.98      6825738.01
#Sta/Elev= 30
  4855.5 2351.57  4858.5 2351.57    4863 2348.84    4869 2349.03    4878 2347.74
  4880.9 2347.89    4884 2348.06  4891.5  2346.1  4920.1 2342.71  4935.1 2339.59
  4950.1 2338.15  4971.2 2332.66  4975.2 2332.24  4975.4 2331.74  4978.9 2331.74
  4979.2 2332.24  4986.2 2332.77  4996.8    2335  5002.7    2335  5013.5 2337.92
  5022.4 2338.37  5051.6 2342.03  5067.8 2342.52  5073.5 2343.31  5089.7 2343.58
  5101.9 2344.51  5111.6 2344.09  5124.6 2345.41  5133.5 2345.51  5147.3 2346.65
#Mann= 4 ,-1 , 0
  4855.5    .035       0  4880.9     .07       0  4975.2     .07       0
  4979.2     .07       0
Bank Sta=4975.2,4979.2
XS Rating Curve= 0 ,0
Exp/Cntr=0.3,0.1

Type RM Length L Ch R = 1 ,27795   ,499,499,499
BEGIN DESCRIPTION:
Finn Creek 47.0
END DESCRIPTION:
XS GIS Cut Line= 3
      1358954.95        6826238.       1359144.5      6826228.21
      1359204.97      6826188.02
#Sta/Elev= 30
  4810.2 2339.82  4812.7 2339.82  4820.3 2339.43  4850.3 2338.26  4880.3 2336.73
  4890.4 2335.93  4900.4 2335.77  4906.3 2335.57  4911.3 2335.15  4920.4 2334.57
  4930.4 2333.45  4940.4 2330.24  4950.4 2327.61  4960.4 2325.45  4970.5 2325.17
  4978.5 2324.64  4978.7 2324.14  4982.2 2324.14  4982.5 2324.64  4997.7 2327.29
  5003.3 2327.29    5008 2328.54    5014 2329.91    5023 2332.77  5044.1  2335.7
  5050.1 2336.37  5059.1 2338.78  5065.1 2338.87  5069.6 2340.32  5072.6 2340.32
#Mann= 3 ,-1 , 0
  4810.2     .07       0  4978.5     .07       0  4982.5     .07       0
Bank Sta=4978.5,4982.5
XS Rating Curve= 0 ,0
Exp/Cntr=0.3,0.1

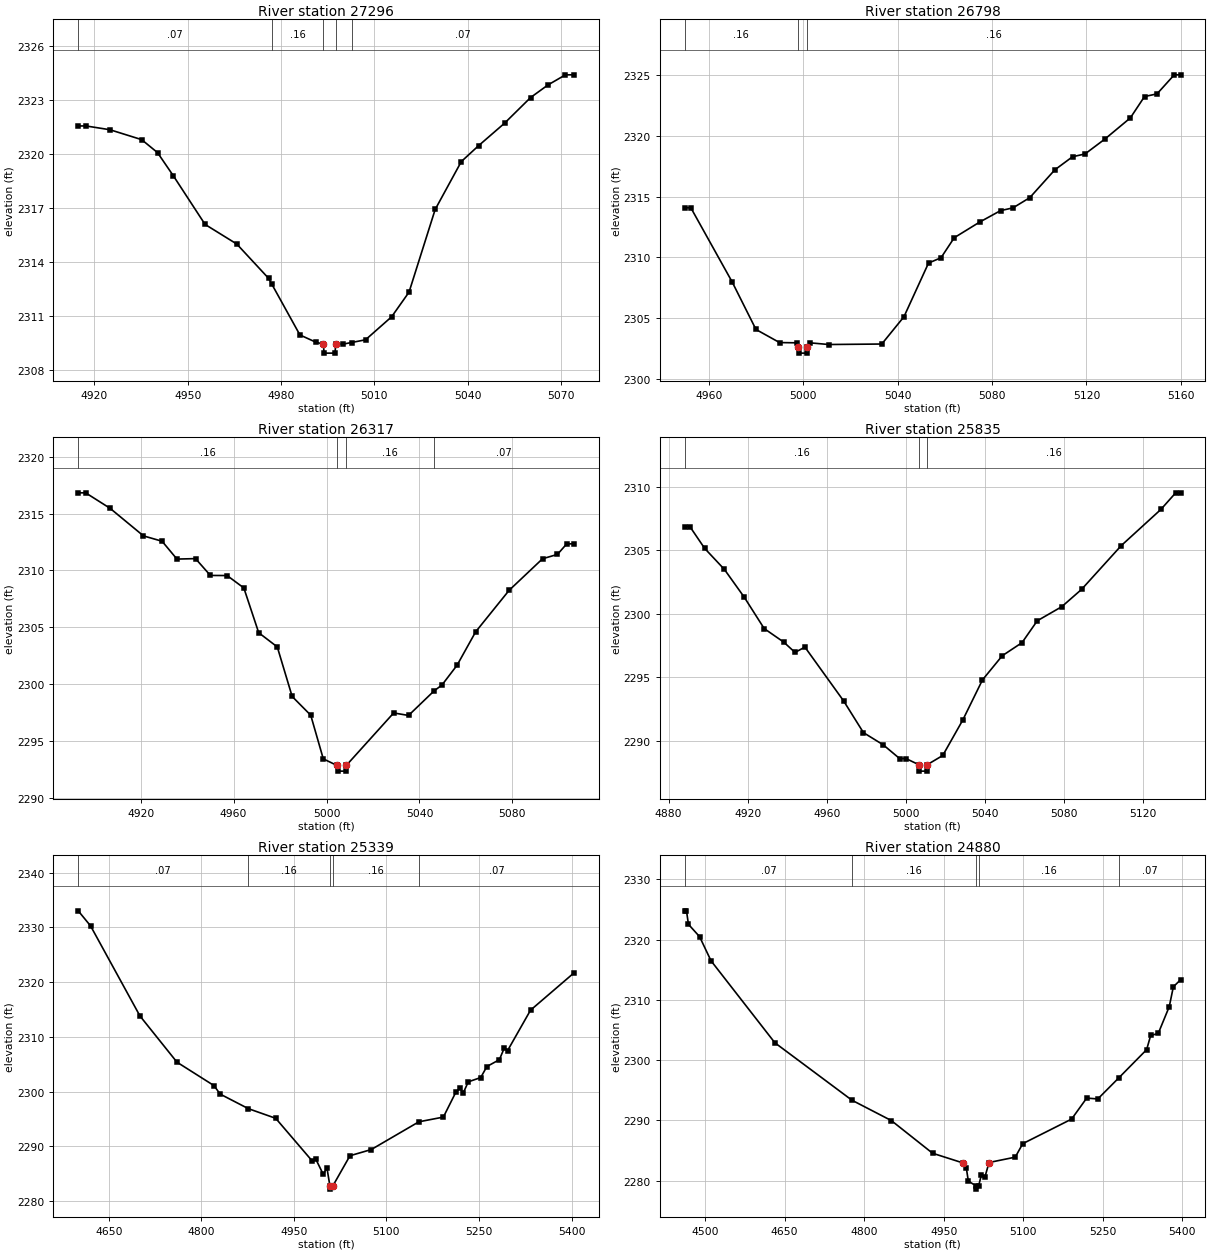
Type RM Length L Ch R = 1 ,27296   ,498,498,498
BEGIN DESCRIPTION:
Finn Creek 46.0
END DESCRIPTION:
XS GIS Cut Line= 3
      1359005.01        6826688.      1359088.54      6826704.75
      1359154.99        6826738.
#Sta/Elev= 29
  4914.8 2321.57  4917.3 2321.57    4925 2321.36  4935.2 2320.81  4940.3 2320.09
  4945.4  2318.8  4955.6  2316.1  4965.8 2315.01    4976 2313.11  4977.1 2312.77
  4986.1 2309.96  4991.2 2309.56  4993.6 2309.45  4993.9 2308.95  4997.4 2308.95
  4997.6 2309.45    5000 2309.45  5002.7 2309.54  5007.2 2309.69  5015.6 2310.97
  5021.2 2312.34  5029.6 2316.93    5038 2319.59  5043.6 2320.48  5051.9 2321.72
  5060.3 2323.15  5065.9 2323.85  5071.5 2324.41  5074.3 2324.41
#Mann= 5 ,-1 , 0
  4914.8     .07       0  4977.1     .16       0  4993.6     .07       0
  4997.6     .16       0  5002.7     .07       0
Bank Sta=4993.6,4997.6
XS Rating Curve= 0 ,0
Exp/Cntr=0.3,0.1

Type RM Length L Ch R = 1 ,26798   ,481,481,481
BEGIN DESCRIPTION:
Finn Creek 45.0
END DESCRIPTION:
XS GIS Cut Line= 3
      1358854.96        6827138.      1358904.91      6827132.96
      1359055.03      6827188.01
#Sta/Elev= 30
  4949.8 2314.08  4952.4 2314.08  4969.9 2307.97    4980 2304.05    4990 2302.97
  4997.3 2302.95  4997.8  2302.6  4998.1  2302.1  5001.6  2302.1  5001.8  2302.6
  5002.8 2302.95  5010.8 2302.81  5033.3 2302.85  5042.7  2305.1  5053.1 2309.52
  5058.4 2309.96    5064 2311.61  5074.7 2312.89  5083.6 2313.84  5088.9 2314.07
    5096 2314.91  5106.6  2317.2  5114.1 2318.28  5119.4 2318.51  5127.9 2319.75
  5138.6 2321.48  5144.6 2323.24  5149.9 2323.46  5157.2 2325.03  5159.9 2325.03
#Mann= 3 ,-1 , 0
  4949.8     .16       0  4997.8     .07       0  5001.8     .16       0
Bank Sta=4997.8,5001.8
XS Rating Curve= 0 ,0
Exp/Cntr=0.3,0.1

Type RM Length L Ch R = 1 ,26317   ,482,482,482
BEGIN DESCRIPTION:
Finn Creek 44.0
END DESCRIPTION:
XS GIS Cut Line= 3
      1358704.97      6827487.96      1358771.81      6827571.39
      1358855.02      6827638.02
#Sta/Elev= 30
  4893.1 2316.83  4896.3 2316.83  4906.8 2315.47  4921.2 2313.04  4929.2 2312.57
  4935.6    2311  4943.6 2311.04    4950 2309.56  4957.2 2309.55  4964.4 2308.46
  4970.8 2304.52  4978.8 2303.27  4985.2 2298.91  4993.2 2297.26  4998.6 2293.42
  5004.5 2292.84  5004.8 2292.34  5008.3 2292.34  5008.5 2292.84  5028.9 2297.46
  5035.3 2297.24  5046.3  2299.4  5049.7 2299.92  5056.2 2301.66  5064.2  2304.6
  5078.6 2308.25    5093 2311.03  5099.4 2311.41  5103.4 2312.34  5106.6 2312.34
#Mann= 4 ,-1 , 0
  4893.1     .16       0  5004.5     .07       0  5008.5     .16       0
  5046.3     .07       0
Bank Sta=5004.5,5008.5
XS Rating Curve= 0 ,0
Exp/Cntr=0.3,0.1

Type RM Length L Ch R = 1 ,25835   ,496,496,496
BEGIN DESCRIPTION:
Finn Creek 43.0
END DESCRIPTION:
XS GIS Cut Line= 3
      1358454.96        6827988.      1358566.42      6827978.07
      1358704.96        6827988.
#Sta/Elev= 30
  4888.1 2306.86  4890.7 2306.86  4898.2 2305.14  4908.2 2303.48  4918.3 2301.28
  4928.3 2298.83  4938.3 2297.75  4943.9 2296.95  4948.9 2297.37  4968.5 2293.13
  4978.5 2290.64  4988.5 2289.68  4996.8  2288.6    5000  2288.6  5006.6 2288.11
  5006.8 2287.61  5010.4 2287.61  5010.7 2288.11  5018.6 2288.84  5028.7 2291.62
  5038.7 2294.79  5048.7 2296.69  5058.7 2297.72  5066.4 2299.44  5078.8 2300.55
  5088.8 2301.91  5108.9 2305.36  5128.9  2308.2  5136.4 2309.51  5138.9 2309.51
#Mann= 3 ,-1 , 0
  4888.1     .16       0  5006.6     .07       0  5010.7     .16       0
Bank Sta=5006.6,5010.7
XS Rating Curve= 0 ,0
Exp/Cntr=0.3,0.1

Type RM Length L Ch R = 1 ,25339   ,459,459,459
BEGIN DESCRIPTION:
Finn Creek 42.0
END DESCRIPTION:
XS GIS Cut Line= 3
      1358154.96        6828438.      1358554.52       6828443.2
      1358955.04        6828388.
#Sta/Elev= 30
  4600.4 2333.02  4620.4 2330.27  4700.5 2313.81  4760.5 2305.37  4820.5 2301.09
  4830.5 2299.54  4876.2 2296.88  4920.5 2295.12  4980.1 2287.27  4985.1 2287.75
  4997.7 2284.86  5003.5 2286.12  5008.5 2282.68  5008.8 2282.18  5012.7 2282.68
  5040.9 2288.28  5075.4 2289.41  5152.6 2294.48  5192.3 2295.34  5212.5 2299.88
  5219.3 2300.65  5224.4 2299.72  5232.7 2301.78  5252.8 2302.56  5262.9 2304.58
  5283.1 2305.83  5291.3 2308.03  5296.3 2307.47  5333.6 2314.87  5404.3 2321.71
#Mann= 5 ,-1 , 0
  4600.4     .07       0  4876.2     .16       0  5008.5     .07       0
  5012.7     .16       0  5152.6     .07       0
Bank Sta=5008.5,5012.7
XS Rating Curve= 0 ,0
Exp/Cntr=0.3,0.1

Type RM Length L Ch R = 1 ,24880   ,494,494,494
BEGIN DESCRIPTION:
Finn Creek 41.0
END DESCRIPTION:
XS GIS Cut Line= 3
      1358204.98      6828487.98       1358605.2      6828848.12
      1358904.99      6828588.01
#Sta/Elev= 30
  4461.6 2324.79    4465 2324.79  4468.7 2322.55  4489.7  2320.5  4511.3 2316.49
  4631.7 2302.88  4777.1 2293.34  4851.4 2289.96  4929.1 2284.54    4986 2282.94
  4992.7 2282.12  4996.5 2279.93  5011.6 2279.08  5011.9 2278.58  5015.8 2279.08
  5021.3 2280.97    5028 2280.64  5035.6    2283    5085 2283.89  5099.2 2286.13
  5191.3 2290.21  5219.8  2293.7  5240.7 2293.55  5280.6 2297.08  5332.8 2301.74
  5340.4 2304.09  5354.7 2304.43  5375.5 2308.89  5383.2 2312.18  5396.9 2313.35
#Mann= 5 ,-1 , 0
  4461.6     .07       0  4777.1     .16       0  5011.6     .07       0
  5015.8     .16       0  5280.6     .07       0
Bank Sta=4986,5035.6
XS Rating Curve= 0 ,0
Exp/Cntr=0.3,0.1

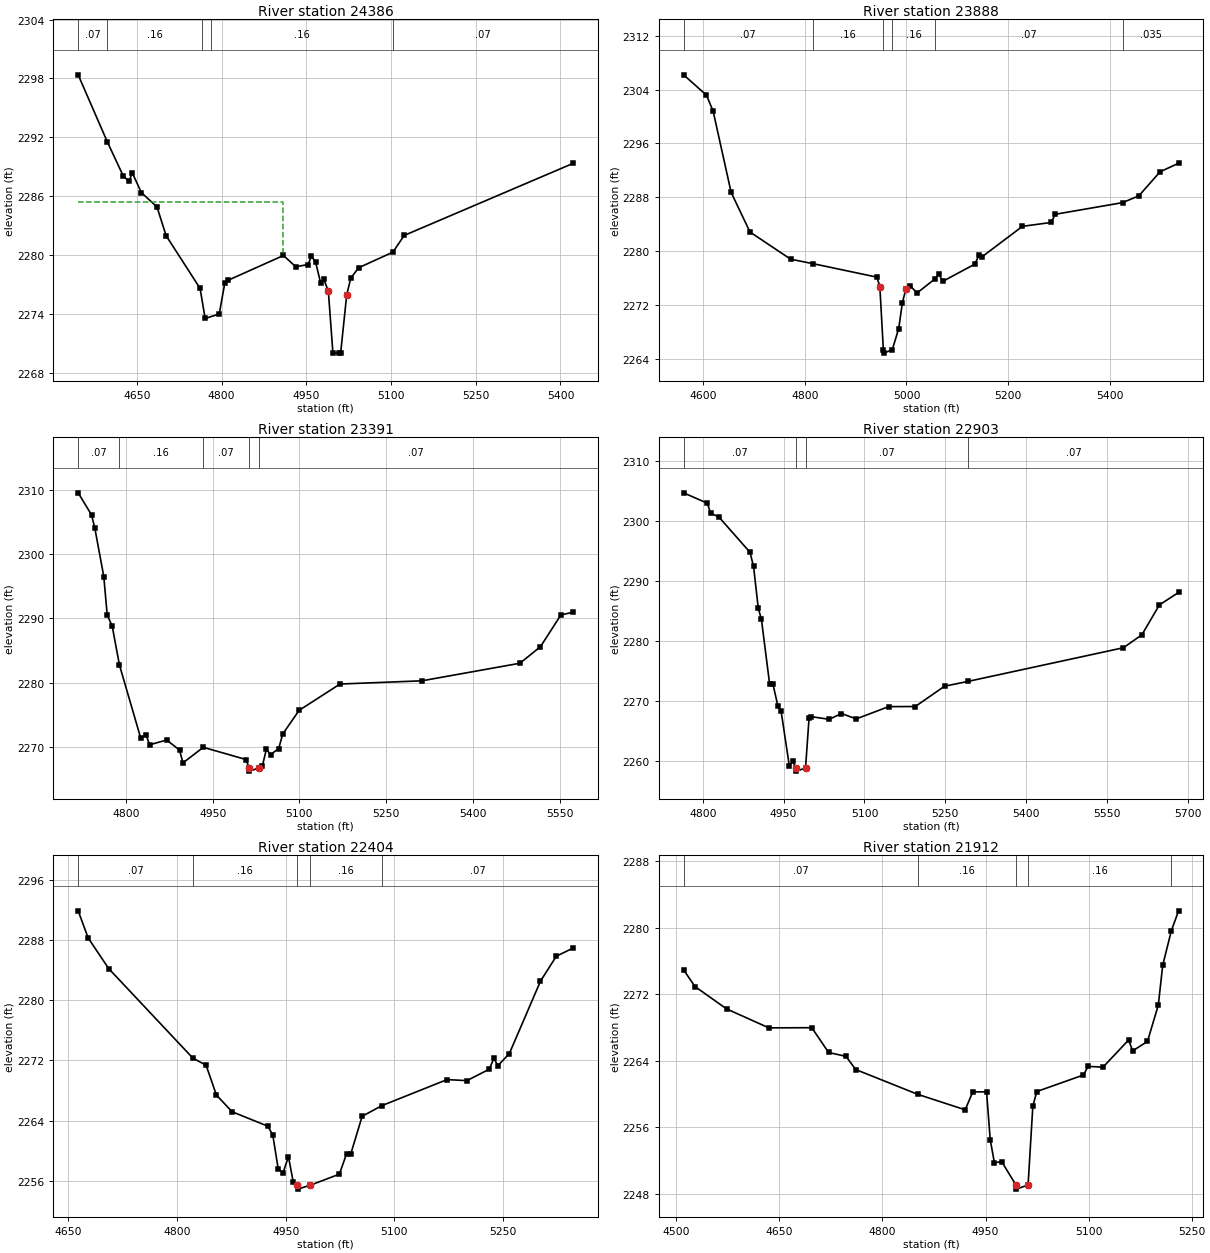
Type RM Length L Ch R = 1 ,24386   ,498,498,498
BEGIN DESCRIPTION:
Finn Creek 40.0
END DESCRIPTION:
XS GIS Cut Line= 3
      1357955.02      6829437.99      1358354.57      6829222.82
      1358754.99        6829088.
#Sta/Elev= 30
  4546.2 2298.37  4597.8 2291.54  4625.7  2288.1  4636.2  2287.5  4641.9  2288.4
  4658.1 2286.37  4685.7 2284.91  4701.9 2281.98    4762 2276.61 4771.01 2273.54
    4796    2274  4805.8 2277.16  4811.4 2277.43  4909.6 2279.96  4931.5 2278.81
  4953.4 2279.04  4959.1 2279.89  4966.4 2279.31  4975.3  2277.2    4981 2277.54
  4989.1 2276.33  4997.2 2270.02 5007.66 2270.01 5010.86 2270.01  5021.6 2275.94
  5028.8 2277.65  5042.7 2278.71  5103.4  2280.3  5123.3    2282  5422.5 2289.35
#Mann= 5 ,-1 , 0
  4546.2     .07       0  4597.8     .16       0  4765.6     .07       0
    4781     .16       0  5103.4     .07       0
#XS Ineff= 2 , 0
         4909.24 2285.43
Permanent Ineff=
       F       F
Bank Sta=4989.1,5021.6
XS Rating Curve= 0 ,0
Exp/Cntr=0.3,0.1

Type RM Length L Ch R = 1 ,23888   ,497,497,497
BEGIN DESCRIPTION:
Finn Creek 39.0
END DESCRIPTION:
XS GIS Cut Line= 3
      1358304.99      6829938.01      1358528.52      6829560.99
      1358955.01      6829237.99
#Sta/Elev= 30
  4561.7  2306.2  4606.6 2303.18  4619.8 2300.79  4655.2 2288.71  4692.3 2282.82
  4772.2 2278.78  4815.9 2278.12  4941.8 2276.11  4947.6 2274.71  4954.5 2265.31
    4955 2264.81    4972 2265.31  4984.7 2268.46  4991.9 2272.31  4998.8 2274.33
  5007.6 2274.81  5020.7 2273.75  5055.7 2275.83  5063.8 2276.63  5070.9 2275.47
  5134.5 2278.05  5142.8 2279.45  5149.1 2279.17  5228.1 2283.67  5284.3 2284.24
  5292.6 2285.46  5424.8 2287.19    5457 2288.21  5498.6 2291.78    5535 2293.05
#Mann= 6 ,-1 , 0
  4561.7     .07       0  4815.9     .16       0  4954.5     .07       0
    4972     .16       0  5055.7     .07       0  5424.8    .035       0
Bank Sta=4947.6,4998.8
XS Rating Curve= 0 ,0
Exp/Cntr=0.3,0.1

Type RM Length L Ch R = 1 ,23391   ,488,488,488
BEGIN DESCRIPTION:
Finn Creek 38.0
END DESCRIPTION:
XS GIS Cut Line= 3
      1358554.99      6830188.01      1358704.25      6829948.04
      1359105.03      6829537.97
#Sta/Elev= 30
  4717.4 2309.57  4740.5 2306.14  4746.3 2304.03  4761.7 2296.53  4767.6 2290.55
  4776.3 2288.79  4788.7 2282.77  4825.4 2271.41  4834.9 2271.86  4840.8 2270.31
  4870.5 2271.06  4892.7 2269.49  4898.6 2267.49  4933.8 2269.92  5007.6 2268.02
    5013 2266.71  5013.5 2266.21  5030.5 2266.71  5035.9 2266.98  5042.9 2269.63
  5050.1 2268.79  5064.2 2269.73  5071.2    2272  5099.5 2275.68  5170.2 2279.78
  5311.7 2280.28  5481.4 2283.02  5516.9  2285.6  5552.1 2290.53  5573.4 2290.98
#Mann= 5 ,-1 , 0
  4717.4     .07       0  4788.7     .16       0  4933.8     .07       0
    5013     .07       0  5030.5     .07       0
Bank Sta=5013,5030.5
XS Rating Curve= 0 ,0
Exp/Cntr=0.3,0.1

Type RM Length L Ch R = 1 ,22903   ,499,499,499
BEGIN DESCRIPTION:
Finn Creek 37.0
END DESCRIPTION:
XS GIS Cut Line= 3
        1359055.      6830487.99        1358930.       6830288.4
      1359254.99      6829688.02
#Sta/Elev= 30
  4764.5 2304.64  4808.7  2302.9  4814.6 2301.23  4829.9 2300.63  4887.7 2294.73
  4894.3 2292.38    4903 2285.43  4908.9 2283.56  4924.2 2272.72  4930.1 2272.85
  4939.5  2269.1  4945.4 2268.28  4960.7 2259.11  4966.6 2259.95  4973.2 2258.79
  4973.7 2258.29  4990.7 2258.79  4997.3 2267.21    5000 2267.38  5034.6 2266.92
  5057.3 2267.88  5084.9 2266.99  5144.8 2269.03  5194.3 2269.05  5248.5 2272.43
  5292.9 2273.25  5580.4 2278.84  5614.7    2281  5647.1 2285.97  5682.7 2288.05
#Mann= 4 ,-1 , 0
  4764.5     .07       0  4973.2     .07       0  4990.7     .07       0
  5292.9     .07       0
Bank Sta=4973.2,4990.7
XS Rating Curve= 0 ,0
Exp/Cntr=0.3,0.1

Type RM Length L Ch R = 1 ,22404   ,492,492,492
BEGIN DESCRIPTION:
Finn Creek 36.0
END DESCRIPTION:
XS GIS Cut Line= 3
      1359155.03      6830487.97        1359380.       6830237.6
      1359555.02      6829937.97
#Sta/Elev= 30
  4663.4 2291.85  4677.2 2288.25  4705.6 2284.18  4821.7 2272.31  4840.1 2271.35
  4854.3  2267.4    4876 2265.18  4925.4 2263.26  4932.2 2262.08  4939.6 2257.64
  4946.3 2257.06  4953.8 2259.23  4960.5 2255.82  4965.9 2255.41  4966.4 2254.91
  4983.5 2255.41  5024.2  2256.9  5034.1 2259.62  5039.9 2259.59  5055.6 2264.58
  5082.8 2265.99  5172.9 2269.45  5200.2 2269.31  5231.2 2270.83  5237.4 2272.25
  5243.2 2271.31  5258.9 2272.91  5301.9 2282.52  5323.8 2285.83    5347 2286.91
#Mann= 5 ,-1 , 0
  4663.4     .07       0  4821.7     .16       0  4965.9     .07       0
  4983.5     .16       0  5082.8     .07       0
Bank Sta=4965.9,4983.5
XS Rating Curve= 0 ,0
Exp/Cntr=0.3,0.1

Type RM Length L Ch R = 1 ,21912   ,387,387,387
BEGIN DESCRIPTION:
Finn Creek 35.0
END DESCRIPTION:
XS GIS Cut Line= 3
      1359379.34      6830503.56      1359839.94      6830338.15
      1359955.02      6830137.97
#Sta/Elev= 30
  4510.6 2274.96  4527.2 2272.95  4573.2 2270.26  4634.7 2267.98  4697.2    2268
  4721.6 2265.02    4747 2264.55    4761 2262.97  4851.4 2259.98  4920.4 2258.12
  4931.4 2260.28  4951.5 2260.28  4956.8 2254.54  4962.9 2251.75  4973.5 2251.89
  4994.2 2249.08  4994.7 2248.58  5011.9 2249.08  5018.8 2258.55  5024.6 2260.32
  5092.5 2262.31  5099.3 2263.35  5120.9 2263.25  5158.3 2266.53    5164 2265.21
  5185.6 2266.34  5201.4 2270.72  5207.8  2275.5  5220.4 2279.67  5230.9 2282.06
#Mann= 5 ,-1 , 0
  4510.6     .07       0  4851.4     .16       0  4994.2     .07       0
  5011.9     .16       0  5220.4     .07       0
Bank Sta=4994.2,5011.9
XS Rating Curve= 0 ,0
Exp/Cntr=0.3,0.1

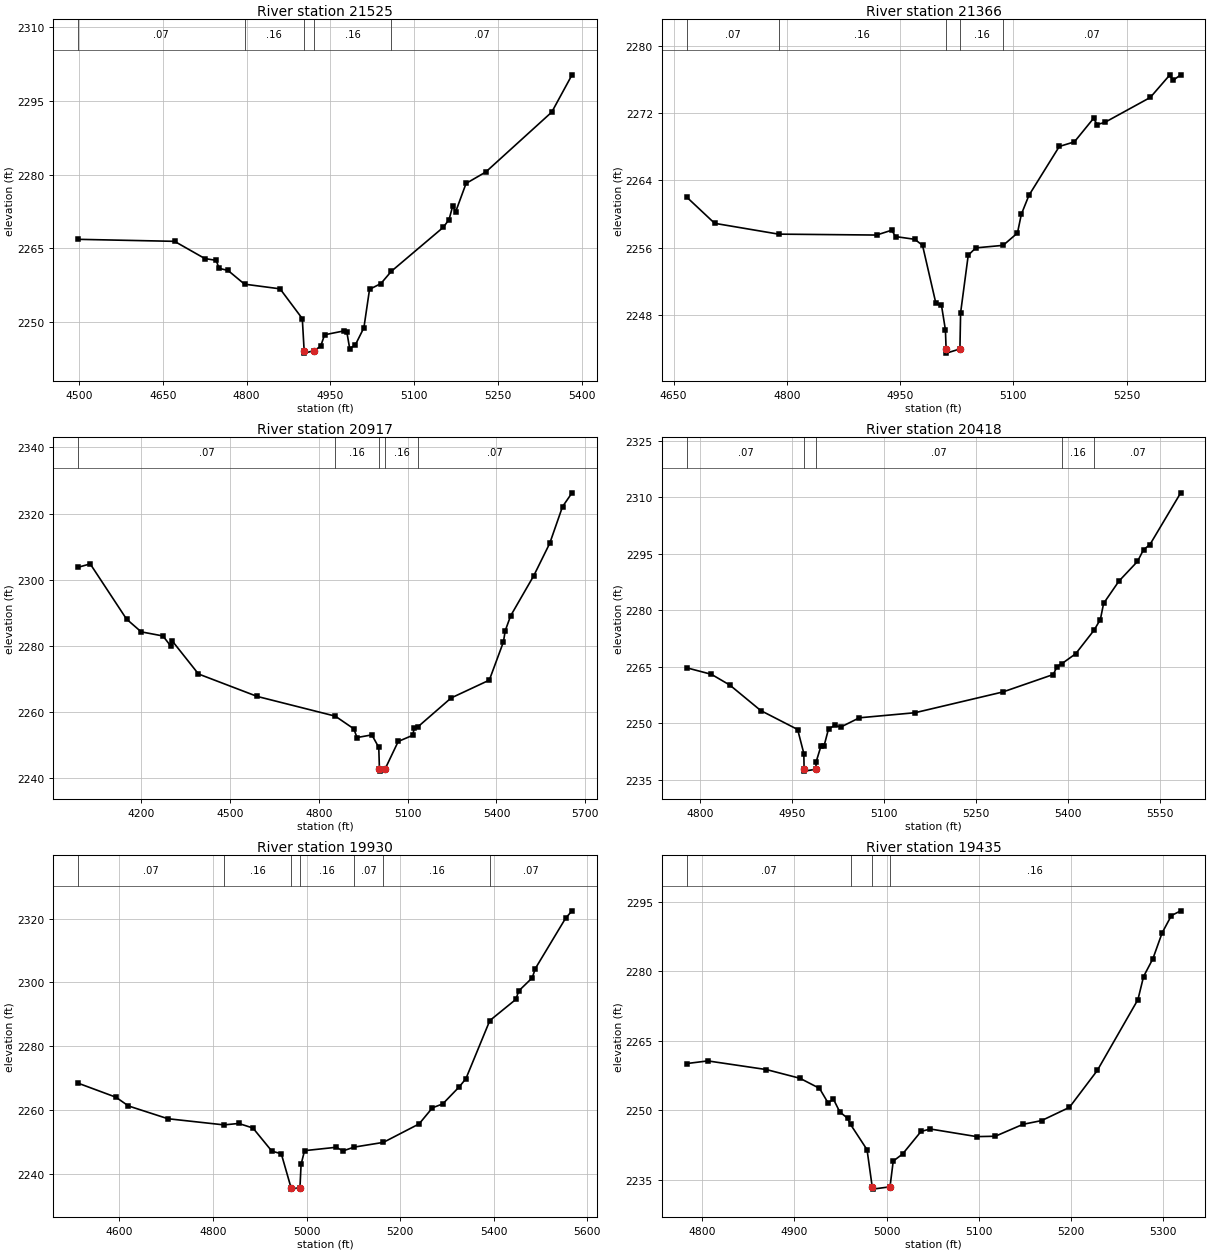
Type RM Length L Ch R = 1 ,21525   ,159,159,159
BEGIN DESCRIPTION:
Finn Creek 34.1
END DESCRIPTION:
XS GIS Cut Line= 3
      1359726.15      6830518.86      1360210.17       6830387.6
      1360277.08       6830011.3
#Sta/Elev= 30
  4498.5 2266.81    4671  2266.4  4725.3 2262.89  4745.5 2262.53  4750.6 2260.91
  4766.7 2260.47  4796.2 2257.68  4859.8 2256.73  4899.6 2250.67  4902.9 2244.14
  4903.4 2243.64  4920.6 2244.14  4932.5 2245.04  4939.4 2247.37  4973.9 2248.16
  4979.2 2247.99  4984.4 2244.56  4994.6 2245.34  5009.8 2248.81  5019.9 2256.63
  5040.2  2257.8    5059 2260.31  5151.9 2269.26  5162.1 2270.83  5168.8 2273.62
  5173.9 2272.39  5192.6 2278.19  5227.8 2280.51  5345.9 2292.71  5382.2  2300.3
#Mann= 5 ,-1 , 0
  4498.5     .07       0  4796.2     .16       0  4902.9     .07       0
  4920.6     .16       0    5059     .07       0
Bank Sta=4902.9,4920.6
XS Rating Curve= 0 ,0
Exp/Cntr=0.3,0.1

Type RM Length L Ch R = 1 ,21366   ,449,449,449
BEGIN DESCRIPTION:
Finn Creek 34.0
END DESCRIPTION:
XS GIS Cut Line= 3
      1359977.37      6830539.89      1360305.04      6830483.45
      1360625.06      6830451.56
#Sta/Elev= 30
  4667.5 2262.01  4704.4 2258.89    4789  2257.6  4918.8 2257.49  4938.9 2258.07
  4943.9 2257.31  4969.5 2256.98  4979.7 2256.26  4997.4 2249.33  5004.8 2249.09
    5010 2246.17  5010.9  2243.9  5011.4  2243.4  5029.2  2243.9  5030.1 2248.21
  5040.2 2255.08  5050.2 2255.96  5086.4 2256.26  5105.4 2257.73  5110.5 2259.96
  5120.6 2262.23  5160.8 2268.06  5180.8 2268.61  5206.1 2271.41  5211.1 2270.68
    5221 2270.93  5281.3 2273.91  5306.8 2276.56  5311.8 2275.97  5321.6 2276.61
#Mann= 5 ,-1 , 0
  4667.5     .07       0    4789     .16       0  5010.9     .07       0
  5029.2     .16       0  5086.4     .07       0
Bank Sta=5010.9,5029.2
XS Rating Curve= 0 ,0
Exp/Cntr=0.3,0.1

Type RM Length L Ch R = 1 ,20917   ,499,499,499
BEGIN DESCRIPTION:
Finn Creek 33.0
END DESCRIPTION:
XS GIS Cut Line= 3
      1359054.96      6830537.99      1360045.22      6830748.54
      1360654.99        6830988.
#Sta/Elev= 30
  3987.6 2303.77  4028.5 2304.78    4151  2288.1  4200.6 2284.23  4273.9 2282.99
  4299.8 2280.01  4304.9 2281.54  4393.9 2271.49  4592.3  2264.7  4855.8 2258.74
    4918 2254.93  4929.3 2252.27  4979.3 2253.07  5002.6 2249.29  5004.9 2242.61
  5005.4 2242.11  5023.2 2242.61  5068.3 2251.09  5117.1 2252.94  5122.5 2255.15
  5134.9 2255.52  5246.9 2264.24  5375.8 2269.63  5423.4 2281.17  5429.5 2284.56
  5447.8 2289.08  5526.2 2301.27  5579.9 2311.03  5622.9 2322.09  5655.1 2326.28
#Mann= 5 ,-1 , 0
  3987.6     .07       0  4855.8     .16       0  5004.9     .07       0
  5023.2     .16       0  5134.9     .07       0
Bank Sta=5004.9,5023.2
XS Rating Curve= 0 ,0
Exp/Cntr=0.3,0.1

Type RM Length L Ch R = 1 ,20418   ,488,488,488
BEGIN DESCRIPTION:
Finn Creek 32.0
END DESCRIPTION:
XS GIS Cut Line= 3
        1359755.        6831088.      1359975.41      6831107.83
      1360555.02        6831038.
#Sta/Elev= 30
  4778.7 2264.73  4818.9    2263    4849 2260.13  4899.2 2253.38  4959.4 2248.34
  4969.5 2241.95  4969.9 2237.78  4970.4 2237.28  4989.1 2237.78  4989.5 2239.72
  4997.3 2243.89  5002.3 2243.89  5009.7 2248.49  5019.7 2249.41  5029.8    2249
    5060 2251.45  5150.7  2252.8    5294 2258.32    5376 2262.95  5382.3 2265.06
  5389.6 2265.78  5412.6 2268.47  5442.3 2274.68  5452.8 2277.55  5458.1 2281.85
  5483.1 2287.77  5513.3 2292.99  5523.3 2296.15  5533.4 2297.42  5583.8 2311.23
#Mann= 5 ,-1 , 0
  4778.7     .07       0  4969.9     .07       0  4989.1     .07       0
  5389.6     .16       0  5442.3     .07       0
Bank Sta=4969.9,4989.1
XS Rating Curve= 0 ,0
Exp/Cntr=0.3,0.1

Type RM Length L Ch R = 1 ,19930   ,495,495,495
BEGIN DESCRIPTION:
Finn Creek 31.0
END DESCRIPTION:
XS GIS Cut Line= 3
      1359755.03        6831538.       1360238.5      6831470.95
      1360604.97      6831038.04
#Sta/Elev= 30
  4511.9 2268.43  4592.6 2264.04  4619.5 2261.29  4703.7 2257.29  4823.4 2255.36
  4855.1  2255.8  4885.4 2254.38  4925.8 2247.13    4946 2246.31  4966.7 2235.72
  4967.2 2235.22  4985.9 2235.72  4988.3    2243  4995.7 2247.28  5063.5 2248.34
  5077.8  2247.2  5101.5 2248.39    5164 2249.87  5240.4 2255.66  5268.9 2260.71
    5291 2261.94  5326.1 2267.27  5340.4 2269.83  5391.5 2288.06    5447 2294.68
  5453.5 2297.38  5482.1 2301.45  5488.7 2304.35  5553.6 2320.18  5567.2 2322.46
#Mann= 7 ,-1 , 0
  4511.9     .07       0  4823.4     .16       0  4966.7     .07       0
  4985.9     .16       0  5101.5     .07       0    5164     .16       0
  5391.5     .07       0
Bank Sta=4966.7,4985.9
XS Rating Curve= 0 ,0
Exp/Cntr=0.3,0.1

Type RM Length L Ch R = 1 ,19435   ,496,496,496
BEGIN DESCRIPTION:
Finn Creek 30.0
END DESCRIPTION:
XS GIS Cut Line= 3
      1360505.02      6831887.97      1360621.49       6831705.1
        1360655.      6831387.97
#Sta/Elev= 30
  4783.2  2260.1    4806 2260.67  4869.5  2258.8  4905.9 2256.92  4927.1 2254.75
  4936.4 2251.61  4942.3 2252.39  4949.1 2249.66  4957.5  2248.3  4960.8 2246.95
  4978.7 2241.49  4984.3 2233.48  4984.8 2232.98  5003.6 2233.48  5007.1 2239.04
  5017.2 2240.55  5037.3 2245.45  5047.4 2245.96  5097.6 2244.32  5117.8  2244.4
  5147.9 2246.98    5168 2247.78  5198.2 2250.64  5228.4  2258.6  5272.5 2273.91
  5278.6 2278.89  5288.7 2282.73  5298.8 2288.35  5308.8 2292.06  5318.9 2293.08
#Mann= 4 ,-1 , 0
  4783.2     .07       0  4960.8     .16       0  4984.3     .07       0
  5003.6     .16       0
Bank Sta=4984.3,5003.6
XS Rating Curve= 0 ,0
Exp/Cntr=0.3,0.1

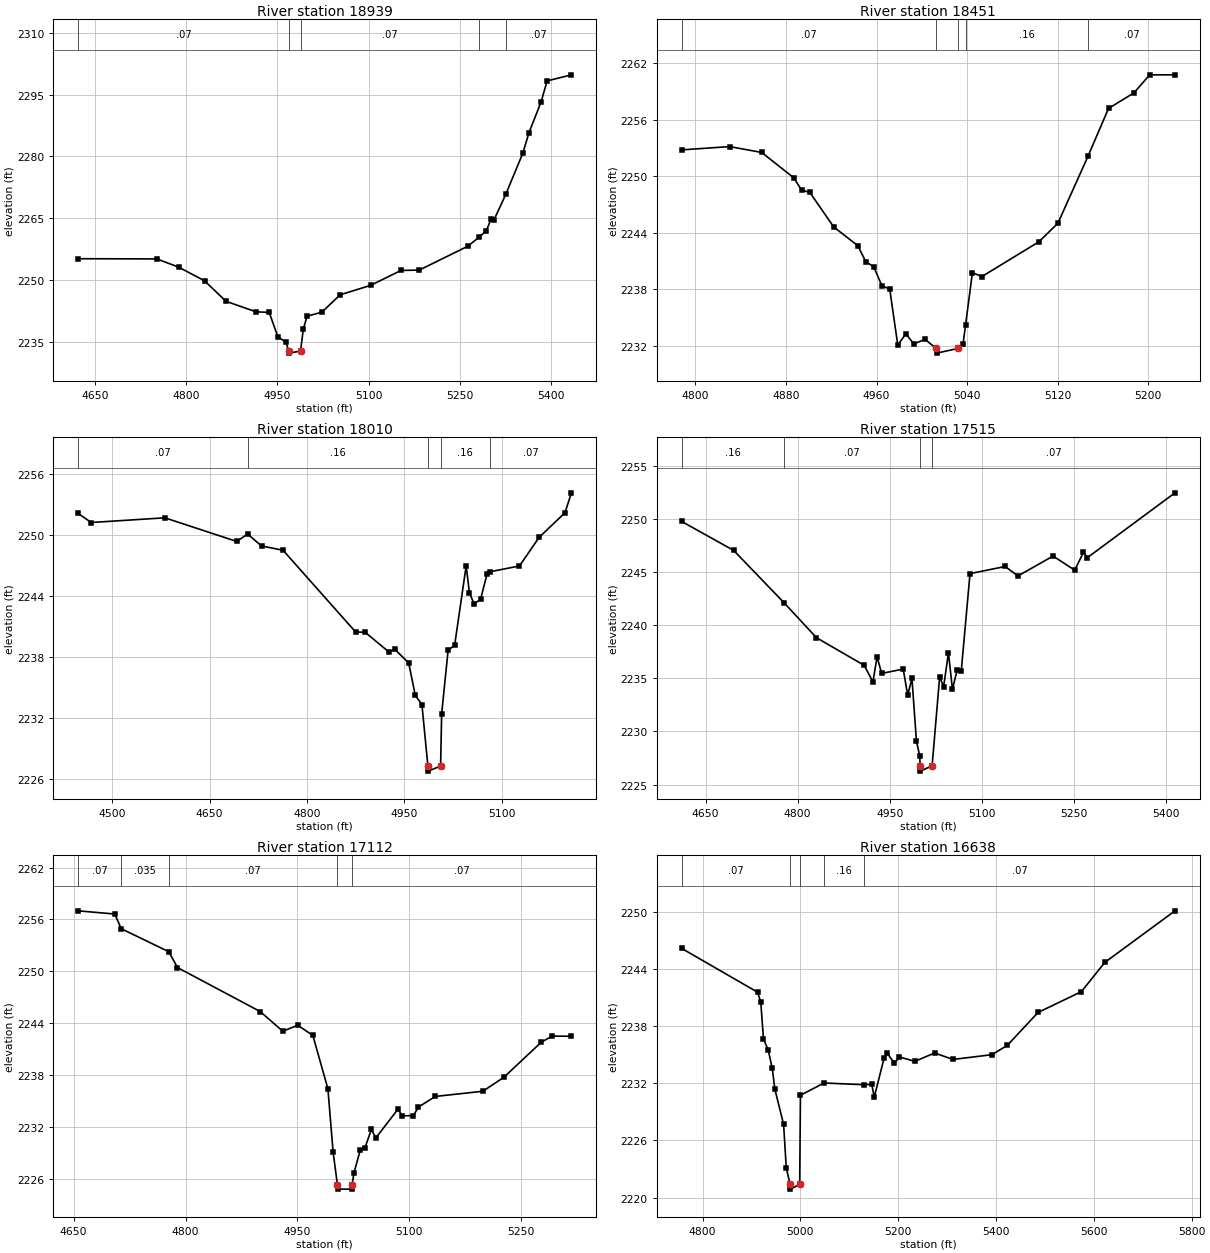
Type RM Length L Ch R = 1 ,18939   ,488,488,488
BEGIN DESCRIPTION:
Finn Creek 29.0
END DESCRIPTION:
XS GIS Cut Line= 3
       1360787.2      6832153.25      1361038.23      6831871.31
        1361055.      6831438.04
#Sta/Elev= 30
  4622.5 2255.23  4751.9 2255.18  4787.8 2253.19  4830.4 2249.87  4865.6 2244.92
  4914.9 2242.36  4936.7 2242.22  4950.9  2236.3  4964.3    2235  4968.8 2232.85
  4969.3 2232.35  4988.2 2232.85  4992.7  2238.1  4998.9 2241.29  5023.3 2242.28
  5053.4 2246.49  5103.4 2248.77  5153.4 2252.39  5183.4 2252.47  5263.5 2258.28
  5281.6 2260.44  5293.5 2261.95  5301.5 2264.88  5306.5 2264.71  5325.5  2270.8
  5353.6 2280.78  5363.6  2285.7  5383.6  2293.2  5393.6 2298.32  5433.6 2299.79
#Mann= 5 ,-1 , 0
  4622.5     .07       0  4968.8     .07       0  4988.2     .07       0
  5281.6     .16       0  5325.5     .07       0
Bank Sta=4968.8,4988.2
XS Rating Curve= 0 ,0
Exp/Cntr=0.3,0.1

Type RM Length L Ch R = 1 ,18451   ,441,441,441
BEGIN DESCRIPTION:
Finn Creek 28.0
END DESCRIPTION:
XS GIS Cut Line= 3
      1361205.01      6832237.99      1361355.03      6832087.92
      1361454.99      6831888.02
#Sta/Elev= 30
  4787.8 2252.79  4830.2 2253.14  4858.5 2252.52  4886.8 2249.83  4893.9  2248.5
  4900.9  2248.3  4922.1 2244.61  4943.4 2242.62  4950.4 2240.93  4957.5 2240.38
  4964.6 2238.38  4971.6 2238.01  4978.7 2232.06  4985.8 2233.26  4992.9 2232.19
  5002.8 2232.67  5012.6 2231.71  5013.1 2231.21    5032 2231.71  5036.3 2232.13
  5038.6 2234.24  5044.6 2239.75    5053 2239.34  5103.3 2243.03  5120.1    2245
  5146.6 2252.09  5164.8 2257.19  5187.2 2258.84  5201.2 2260.76  5223.5 2260.76
#Mann= 5 ,-1 , 0
  4787.8     .07       0  5012.6     .07       0    5032     .07       0
  5038.6     .16       0  5146.6     .07       0
Bank Sta=5012.6,5032
XS Rating Curve= 0 ,0
Exp/Cntr=0.3,0.1

Type RM Length L Ch R = 1 ,18010   ,495,495,495
BEGIN DESCRIPTION:
Finn Creek 27.0
END DESCRIPTION:
XS GIS Cut Line= 3
      1361204.98        6832338.      1361747.32      6832231.48
      1361955.02        6832238.
#Sta/Elev= 30
  4447.3 2252.09  4467.7  2251.2    4581 2251.66  4691.9 2249.34  4708.6 2250.07
  4730.1  2248.9  4763.2 2248.48  4875.3 2240.45  4889.5 2240.45  4926.3 2238.51
  4935.8 2238.75  4956.9 2237.43  4967.1 2234.24  4977.3 2233.35  4986.5 2227.32
    4987 2226.82  5006.1 2227.32  5007.7 2232.43  5017.7 2238.69  5027.7 2239.15
  5045.5 2246.95  5050.5 2244.31  5057.7 2243.23  5067.7 2243.66  5077.7 2246.16
  5082.3 2246.37  5127.7 2246.94  5157.8 2249.73  5197.8 2252.16  5207.8 2254.11
#Mann= 5 ,-1 , 0
  4447.3     .07       0  4708.6     .16       0  4986.5     .07       0
  5006.1     .16       0  5082.3     .07       0
Bank Sta=4986.5,5006.1
XS Rating Curve= 0 ,0
Exp/Cntr=0.3,0.1

Type RM Length L Ch R = 1 ,17515   ,403,403,403
BEGIN DESCRIPTION:
Finn Creek 26.0
END DESCRIPTION:
XS GIS Cut Line= 3
      1361504.98      6832437.98      1361788.12      6832704.58
        1362105.        6832438.
#Sta/Elev= 30
  4611.1 2249.75  4695.9 2247.02    4778 2242.09  4830.6 2238.81  4908.3 2236.21
  4922.5 2234.65  4929.3 2237.03  4936.6 2235.45  4971.8 2235.86  4979.1  2233.4
    4986 2234.98  4993.3  2229.1  4998.8 2227.64  4999.2 2226.76  4999.7 2226.26
  5018.8 2226.76  5031.1 2235.13  5037.6 2234.21  5045.4 2237.39  5051.9 2233.96
  5059.7  2235.8  5066.2 2235.65  5080.5 2244.84  5137.7 2245.51  5158.5 2244.62
  5215.7 2246.49  5250.9 2245.17  5265.2 2246.84  5271.7 2246.35  5414.1 2252.44
#Mann= 4 ,-1 , 0
  4611.1     .16       0    4778     .07       0  4999.2     .07       0
  5018.8     .07       0
Bank Sta=4999.2,5018.8
XS Rating Curve= 0 ,0
Exp/Cntr=0.3,0.1

Type RM Length L Ch R = 1 ,17112   ,474,474,474
BEGIN DESCRIPTION:
Finn Creek 25.0
END DESCRIPTION:
XS GIS Cut Line= 3
       1361272.8      6833089.64      1361613.95      6833044.69
      1361871.26      6832858.34
#Sta/Elev= 30
  4655.9 2256.99  4705.1 2256.62  4713.8 2254.92  4777.6 2252.26  4789.2 2250.43
  4900.2 2245.34  4930.4 2243.07  4950.6 2243.75  4970.8 2242.58    4991 2236.41
    4998 2229.07  5003.8  2225.3  5004.3  2224.8  5022.9  2224.8  5023.4  2225.3
    5026 2226.69  5034.6 2229.37  5040.7 2229.58  5049.3  2231.7  5055.4 2230.73
  5084.8 2234.03    5091 2233.28  5105.7  2233.3  5112.4 2234.29  5135.1 2235.52
  5198.8 2236.12  5227.1 2237.74  5277.4 2241.81  5292.1  2242.5  5317.7 2242.48
#Mann= 5 ,-1 , 0
  4655.9     .07       0  4713.8    .035       0  4777.6     .07       0
  5003.8     .07       0  5023.4     .07       0
Bank Sta=5003.8,5023.4
XS Rating Curve= 0 ,0
Exp/Cntr=0.3,0.1

Type RM Length L Ch R = 1 ,16638   ,605,605,605
BEGIN DESCRIPTION:
Finn Creek 24.1
END DESCRIPTION:
XS GIS Cut Line= 3
      1361782.93      6833378.77       1362005.3       6833280.8
       1362238.4      6832551.23
#Sta/Elev= 30
    4757 2246.16  4912.3 2241.56  4918.9 2240.53  4924.4 2236.65  4934.1 2235.49
  4942.3 2233.59  4947.7 2231.38  4965.6 2227.68    4971 2223.11  4978.9 2221.39
  4979.4 2220.89  4998.5 2221.39    5000 2230.74  5048.1 2232.03  5129.5 2231.85
  5145.8 2231.89    5151 2230.56  5170.9 2234.61  5177.9 2235.13  5191.9 2234.11
  5202.4 2234.76  5233.9  2234.3  5274.5 2235.18  5311.9  2234.5  5391.4    2235
  5422.9 2235.97  5485.8 2239.43  5574.6 2241.62  5622.3 2244.68  5765.9  2250.1
#Mann= 5 ,-1 , 0
    4757     .07       0  4978.9     .07       0  4998.5     .07       0
  5048.1     .16       0  5129.5     .07       0
Bank Sta=4978.9,4998.5
XS Rating Curve= 0 ,0
Exp/Cntr=0.3,0.1