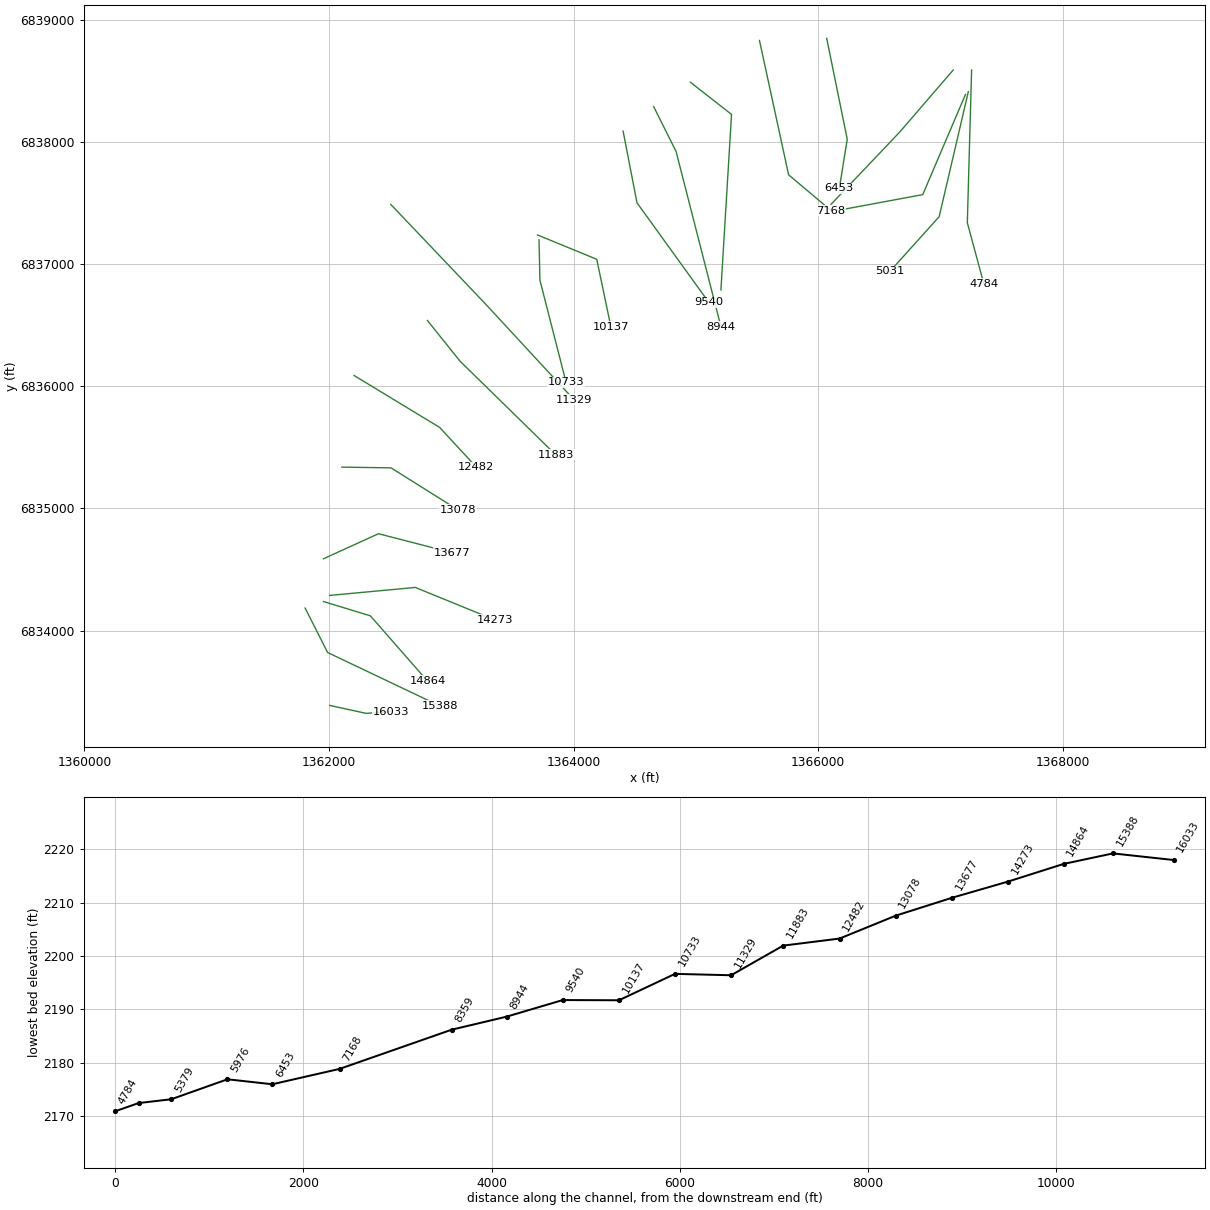
HEC-RAS study Finn Creek.prj: Finn Creek Base Level Engineering

--- Finn Creek.g01 (geometry) --- (continued)

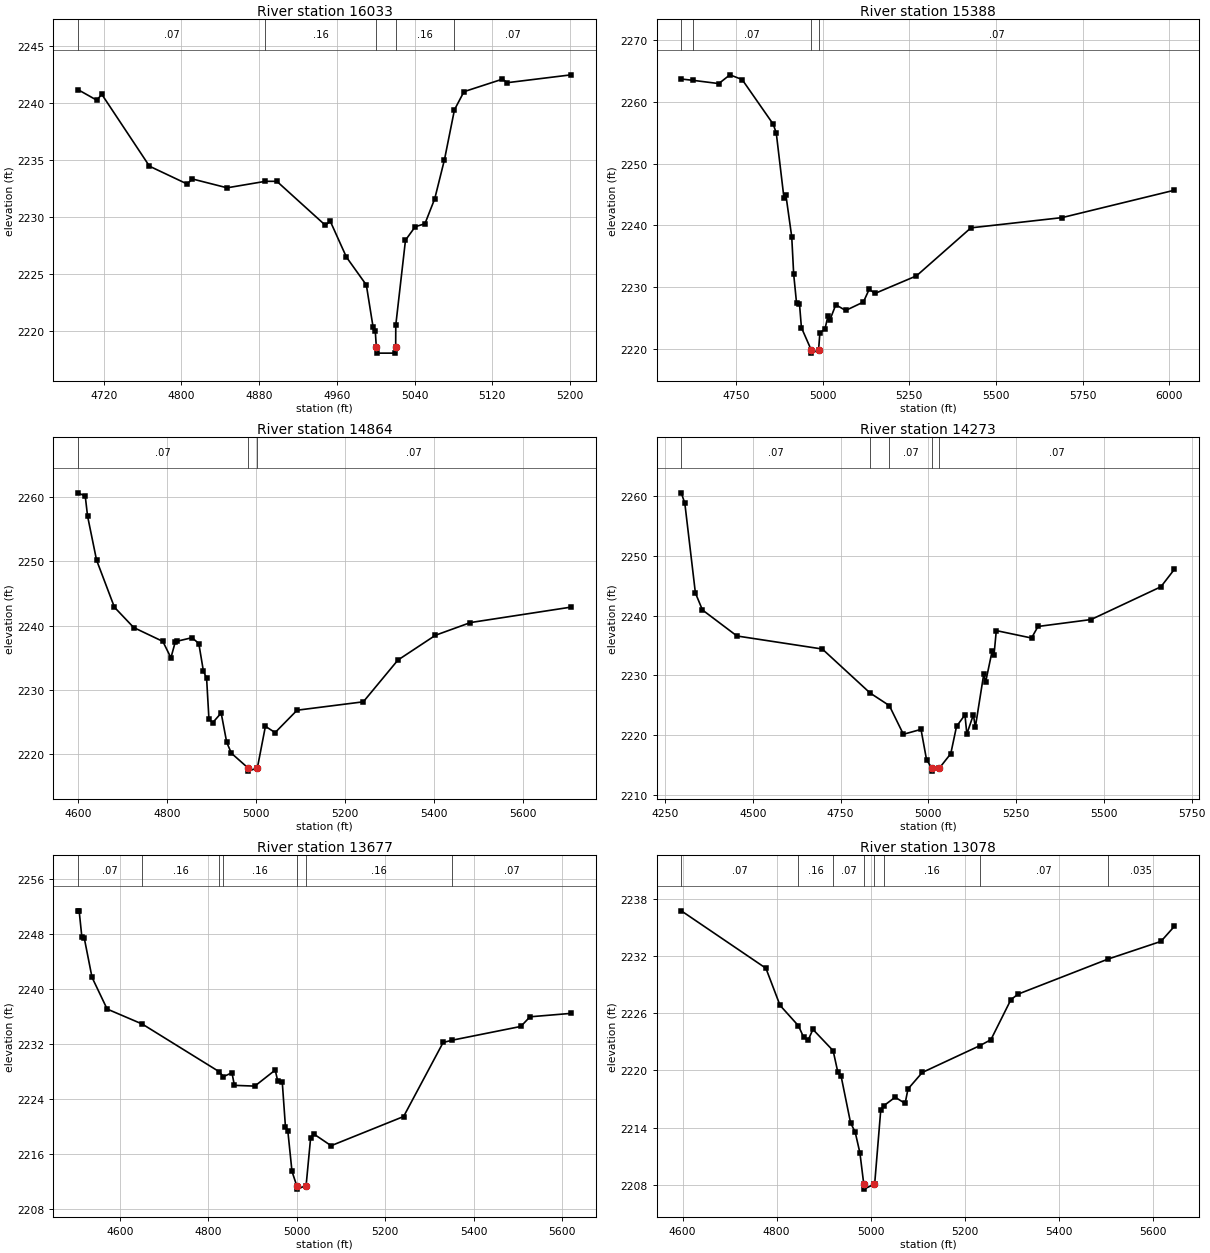
Type RM Length L Ch R = 1 ,16033   ,645,645,645
BEGIN DESCRIPTION:
Finn Creek 24.0
END DESCRIPTION:
XS GIS Cut Line= 3
      1362005.02        6833388.       1362304.5      6833322.79
      1362505.03        6833338.
#Sta/Elev= 30
  4693.5 2241.18  4712.9 2240.25    4718 2240.77  4767.1 2234.45    4806 2232.88
  4811.1 2233.33    4847 2232.55  4886.4 2233.12  4898.2 2233.12  4948.1 2229.26
  4953.2 2229.61  4969.8 2226.46  4990.3 2224.01  4997.2 2220.33  4999.5 2219.97
  5000.6 2218.52  5001.1 2218.02    5020 2218.02  5020.5 2218.52  5020.6 2220.48
  5030.6 2227.95  5040.6 2229.13  5050.6 2229.39  5060.7 2231.59  5070.7 2235.02
    5081 2239.41  5090.8    2241  5130.4  2242.1  5135.4 2241.79  5201.1 2242.48
#Mann= 5 ,-1 , 0
  4693.5     .07       0  4886.4     .16       0  5000.6     .07       0
  5020.5     .16       0    5081     .07       0
Bank Sta=5000.6,5020.5
XS Rating Curve= 0 ,0
Exp/Cntr=0.3,0.1

Type RM Length L Ch R = 1 ,15388   ,524,524,524
BEGIN DESCRIPTION:
Finn Creek 23.0
END DESCRIPTION:
XS GIS Cut Line= 3
      1361804.92      6834184.57      1361988.87      6833820.95
      1362904.93      6833384.54
#Sta/Elev= 30
  4592.5 2263.74  4627.2 2263.52  4700.7    2263  4732.7 2264.42    4768 2263.65
  4857.6 2256.41  4866.4 2254.97  4888.7 2244.37  4894.3 2244.84    4911 2238.13
  4916.6 2232.07  4924.9 2227.37  4933.3  2227.3  4938.9  2223.4  4967.3 2219.76
  4967.8 2219.26  4988.4 2219.76  4992.1 2222.52  5006.8 2223.18  5015.4 2225.25
  5020.9 2224.63  5038.1 2227.11  5066.4 2226.18  5117.6 2227.55  5134.5 2229.64
  5150.8 2228.94  5270.7  2231.8  5427.7 2239.59  5690.4 2241.25  6014.7  2245.7
#Mann= 4 ,-1 , 0
  4592.5    .035       0  4627.2     .07       0  4967.3     .07       0
  4988.4     .07       0
Bank Sta=4967.3,4988.4
XS Rating Curve= 0 ,0
Exp/Cntr=0.3,0.1

Type RM Length L Ch R = 1 ,14864   ,591,591,591
BEGIN DESCRIPTION:
Finn Creek 22.0
END DESCRIPTION:
XS GIS Cut Line= 3
      1361955.04      6834237.99      1362338.48      6834120.97
        1362805.        6833588.
#Sta/Elev= 30
  4599.1 2260.69  4615.5 2260.18  4620.7 2257.07  4640.9 2250.21  4681.1 2242.85
  4724.5 2239.68    4790 2237.52  4808.2 2234.96  4817.6 2237.35  4822.8 2237.56
  4855.6  2238.1  4870.9 2237.19  4881.3 2232.87  4888.4  2231.8  4893.7 2225.41
  4902.3 2224.86  4921.2 2226.35  4933.6  2221.8  4944.1 2220.09  4981.5 2217.79
    4982 2217.29  5002.6 2217.79  5020.7 2224.28  5042.5  2223.3  5091.9 2226.79
  5240.9  2228.1  5318.7 2234.61  5403.2 2238.48  5481.9 2240.46  5708.3 2242.87
#Mann= 3 ,-1 , 0
  4599.1     .07       0  4981.5     .07       0  5002.6     .07       0
Bank Sta=4981.5,5002.6
XS Rating Curve= 0 ,0
Exp/Cntr=0.3,0.1

Type RM Length L Ch R = 1 ,14273   ,596,596,596
BEGIN DESCRIPTION:
Finn Creek 21.0
END DESCRIPTION:
XS GIS Cut Line= 3
      1362004.97        6834288.      1362706.03      6834353.41
      1363354.96      6834088.02
#Sta/Elev= 30
  4295.9 2260.52    4306 2258.76  4336.1 2243.77  4356.2 2240.93  4454.5 2236.58
  4697.7  2234.4  4833.9 2227.04  4888.6 2224.94  4928.7 2220.14  4978.9 2220.96
  4994.7 2215.88  5009.9 2214.48  5010.4 2213.98  5031.1 2214.48  5063.7  2216.9
  5080.1 2221.46  5104.1 2223.39  5109.5 2220.19  5128.2 2223.42  5133.6 2221.29
  5157.6 2230.18    5163 2228.86  5181.6 2234.08    5187 2233.47  5193.4 2237.48
  5293.8 2236.24  5312.2 2238.17  5463.5 2239.33  5662.4 2244.81  5701.1 2247.75
#Mann= 5 ,-1 , 0
  4295.9     .07       0  4833.9     .16       0  4888.6     .07       0
  5009.9     .07       0  5031.1     .07       0
Bank Sta=5009.9,5031.1
XS Rating Curve= 0 ,0
Exp/Cntr=0.3,0.1

Type RM Length L Ch R = 1 ,13677   ,599,599,599
BEGIN DESCRIPTION:
Finn Creek 20.0
END DESCRIPTION:
XS GIS Cut Line= 3
      1361955.02      6834588.01      1362404.83      6834792.96
      1363005.04      6834637.99
#Sta/Elev= 30
  4505.7 2251.38  4508.4 2251.38  4514.5  2247.6    4520 2247.41  4537.5 2241.71
  4571.6 2237.11  4651.2 2234.92  4825.1 2227.99  4834.2 2227.28  4853.6 2227.85
  4859.1 2226.02  4905.2 2225.91  4951.3 2228.24  4956.8 2226.72  4967.2 2226.56
  4974.4 2220.04  4979.8 2219.42  4989.2 2213.53  4999.9 2211.44  5000.4 2210.94
  5021.1 2211.44  5031.2  2218.3  5038.1 2218.97  5077.6 2217.25  5241.4 2221.49
  5330.7 2232.25  5351.8 2232.59  5506.2 2234.58  5526.9 2235.98  5619.9 2236.48
#Mann= 7 ,-1 , 0
  4505.7     .07       0  4651.2     .16       0  4825.1     .07       0
  4834.2     .16       0  4999.9     .07       0  5021.1     .16       0
  5351.8     .07       0
Bank Sta=4999.9,5021.1
XS Rating Curve= 0 ,0
Exp/Cntr=0.3,0.1

Type RM Length L Ch R = 1 ,13078   ,596,596,596
BEGIN DESCRIPTION:
Finn Creek 19.0
END DESCRIPTION:
XS GIS Cut Line= 3
      1362105.01        6835338.      1362507.66      6835331.92
      1363054.99      6834988.01
#Sta/Elev= 30
  4597.3 2236.71  4777.3  2230.7  4807.3 2226.82  4846.6 2224.67  4857.3  2223.5
  4867.3 2223.19  4877.3  2224.3  4920.3 2222.07  4930.3 2219.82  4937.3 2219.39
  4957.3 2214.54  4967.3 2213.53  4977.3 2211.36  4985.5 2208.08    4986 2207.58
  5006.8 2208.08  5008.7 2208.16  5021.6 2215.87  5027.6 2216.29  5052.2  2217.2
  5073.4 2216.55  5079.5 2218.06  5109.9 2219.79  5232.5  2222.6  5255.9 2223.22
  5298.4 2227.41  5313.7 2227.99  5505.1 2231.66  5617.6 2233.51  5646.4  2235.1
#Mann= 8 ,-1 , 0
  4597.3     .07       0  4846.6     .16       0  4920.3     .07       0
  4985.5     .07       0  5006.8     .07       0  5027.6     .16       0
  5232.5     .07       0  5505.1    .035       0
Bank Sta=4985.5,5006.8
XS Rating Curve= 0 ,0
Exp/Cntr=0.3,0.1

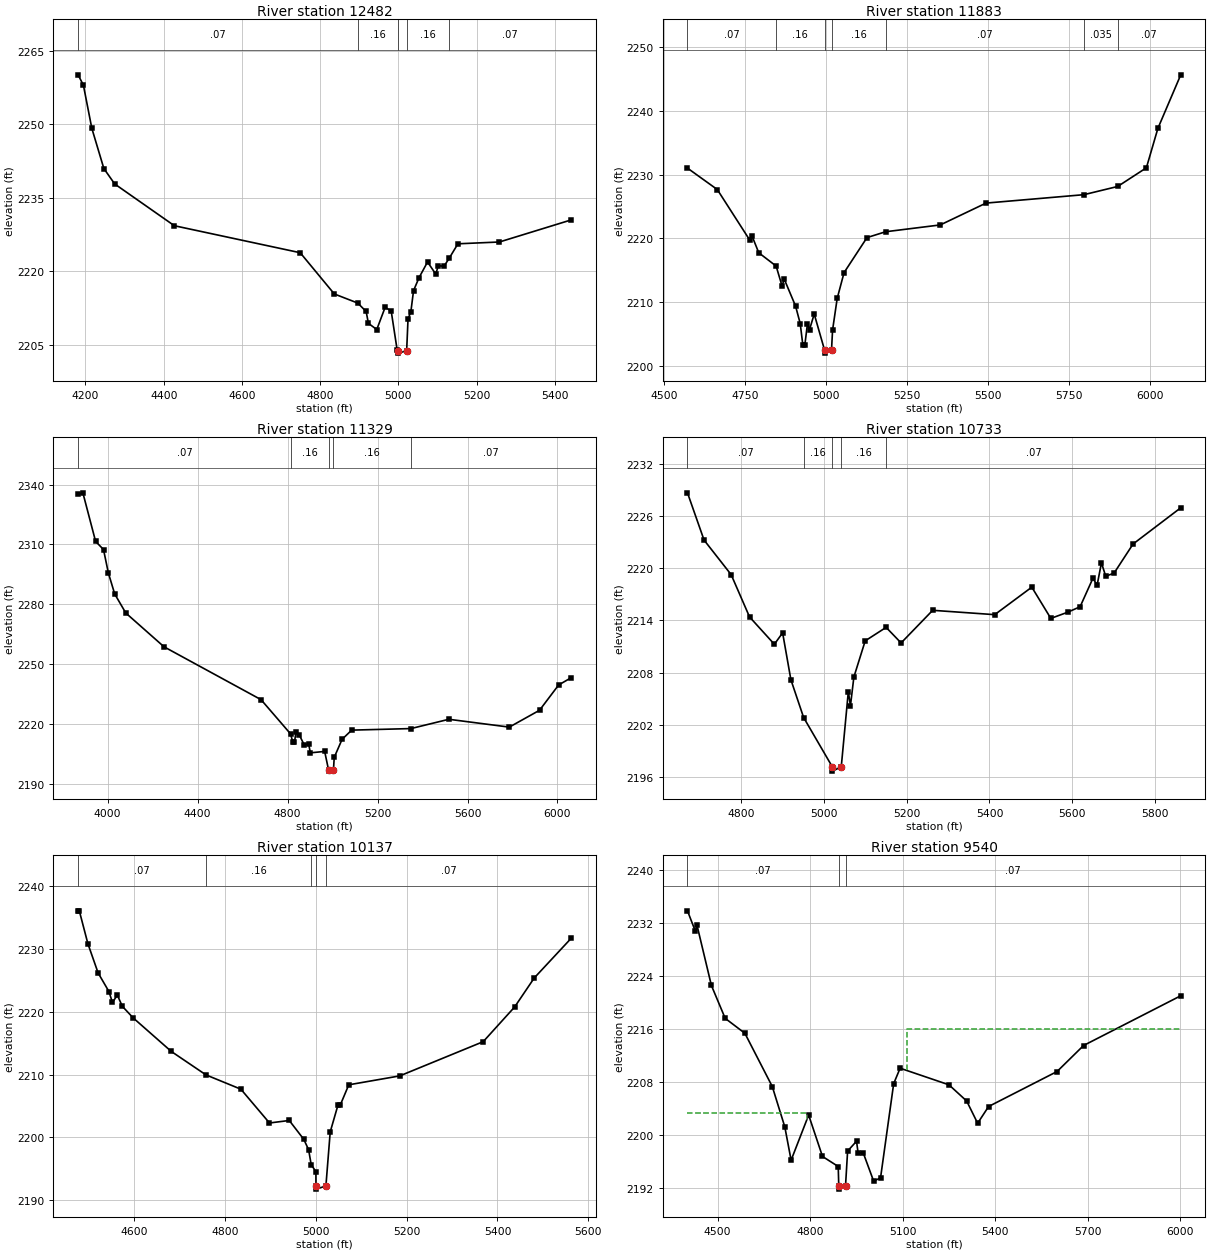
Type RM Length L Ch R = 1 ,12482   ,599,599,599
BEGIN DESCRIPTION:
Finn Creek 18.0
END DESCRIPTION:
XS GIS Cut Line= 3
      1362205.02      6836087.99      1362905.01        6835663.
      1363205.01      6835337.99
#Sta/Elev= 30
  4181.1 2260.11  4194.7    2258  4216.2  2249.2    4247 2240.98  4274.7 2237.83
  4427.3  2229.3    4749 2223.79  4836.2 2215.37  4896.2 2213.51  4917.6 2211.79
  4923.4 2209.37  4944.8 2208.11  4966.1 2212.63  4981.6 2211.92  4997.1 2203.83
  4999.8 2203.79  5000.3 2203.29  5021.2 2203.79  5024.7 2210.25    5032 2211.77
  5038.8 2216.05    5053 2218.72  5074.6  2221.9  5095.5 2219.44  5102.3 2221.15
  5116.5 2221.01  5129.6 2222.61  5152.2 2225.61  5258.3 2225.98  5442.3  2230.5
#Mann= 5 ,-1 , 0
  4181.1     .07       0  4896.2     .16       0  4999.8     .07       0
  5021.2     .16       0  5129.6     .07       0
Bank Sta=4999.8,5021.2
XS Rating Curve= 0 ,0
Exp/Cntr=0.3,0.1

Type RM Length L Ch R = 1 ,11883   ,554,554,554
BEGIN DESCRIPTION:
Finn Creek 17.0
END DESCRIPTION:
XS GIS Cut Line= 3
      1362805.01      6836537.99      1363072.03      6836204.52
      1363854.99      6835438.01
#Sta/Elev= 30
  4572.8 2231.02  4664.8 2227.66  4764.9 2219.73  4772.1 2220.36  4792.9 2217.73
  4846.5 2215.64  4864.9 2212.49  4871.3 2213.62  4906.5 2209.36  4920.9 2206.61
  4928.9 2203.26  4935.3 2203.32  4943.3  2206.6  4949.7 2205.68  4964.1 2208.11
  4995.9 2202.47  4996.4 2201.97  5017.5 2202.47  5020.8 2205.61    5035 2210.55
  5056.2 2214.61    5127 2220.11  5184.5 2221.03  5353.3  2222.1  5494.6 2225.53
  5796.8 2226.85    5901 2228.14  5989.6 2231.07  6025.1 2237.26  6095.7 2245.67
#Mann= 7 ,-1 , 0
  4572.8     .07       0  4846.5     .16       0  4995.9     .07       0
  5017.5     .16       0  5184.5     .07       0  5796.8    .035       0
    5901     .07       0
Bank Sta=4995.9,5017.5
XS Rating Curve= 0 ,0
Exp/Cntr=0.3,0.1

Type RM Length L Ch R = 1 ,11329   ,596,596,596
BEGIN DESCRIPTION:
Finn Creek 16.0
END DESCRIPTION:
XS GIS Cut Line= 3
      1362504.97      6837488.04      1363284.82      6836668.07
      1364005.01      6835887.99
#Sta/Elev= 30
  3868.4 2335.02  3889.7 2335.84  3946.3  2311.5  3981.5 2307.43  4002.9 2295.75
  4031.2 2285.17  4080.6 2275.63  4250.5  2258.7    4682 2232.21  4813.1 2215.08
  4823.2 2210.98  4830.5 2210.94  4837.4 2215.88  4851.5 2214.65    4873 2209.75
    4894 2209.78  4901.3 2205.58  4964.8 2206.28  4982.3 2196.91  4982.8 2196.41
  5003.9 2196.91  5007.3 2203.29  5042.4 2212.37    5085 2216.95  5348.4 2217.73
    5517 2222.38  5785.8 2218.46  5920.2  2226.9  6005.3 2239.59  6061.7 2243.26
#Mann= 5 ,-1 , 0
  3868.4     .07       0  4813.1     .16       0  4982.3     .07       0
  5003.9     .16       0  5348.4     .07       0
Bank Sta=4982.3,5003.9
XS Rating Curve= 0 ,0
Exp/Cntr=0.3,0.1

Type RM Length L Ch R = 1 ,10733   ,596,596,596
BEGIN DESCRIPTION:
Finn Creek 15.0
END DESCRIPTION:
XS GIS Cut Line= 3
      1363717.67      6837198.04      1363724.93      6836867.82
      1363938.82      6836032.16
#Sta/Elev= 30
  4669.7 2228.65  4709.8 2223.22  4775.3 2219.25  4819.8 2214.39  4879.8 2211.25
  4899.8 2212.56  4919.8 2207.17  4950.6 2202.83  5019.9 2197.17  5020.4 2196.67
  5041.6 2197.17  5058.7 2205.82  5063.8 2204.17  5072.1 2207.48  5099.5 2211.64
  5150.1 2213.19  5186.3  2211.4  5262.7 2215.15  5412.7 2214.65  5502.4 2217.81
  5548.4 2214.22  5589.2 2214.93  5619.2 2215.56  5650.1 2218.82  5660.4 2218.05
  5670.8 2220.61  5681.1 2219.07  5701.3 2219.42  5747.3 2222.77  5862.6 2226.93
#Mann= 5 ,-1 , 0
  4669.7     .07       0  4950.6     .16       0  5019.9     .07       0
  5041.6     .16       0  5150.1     .07       0
Bank Sta=5019.9,5041.6
XS Rating Curve= 0 ,0
Exp/Cntr=0.3,0.1

Type RM Length L Ch R = 1 ,10137   ,597,597,597
BEGIN DESCRIPTION:
Finn Creek 14.0
END DESCRIPTION:
XS GIS Cut Line= 3
        1363705.        6837238.      1364189.66      6837038.82
      1364305.01      6836487.96
#Sta/Elev= 30
    4476 2236.11  4478.7 2236.11  4497.6 2230.87  4520.1 2226.21    4544 2223.23
  4551.7 2221.49  4562.5 2222.67  4573.4 2220.89  4597.4 2219.03  4681.4 2213.68
  4757.8 2209.94  4834.7 2207.66  4897.7 2202.27  4941.3 2202.67  4973.3 2199.66
  4983.9 2198.01  4989.6 2195.63    5000  2194.5  5000.1 2192.22  5000.6 2191.72
    5022 2192.22  5031.5 2200.84  5048.6 2205.13  5053.7 2205.14  5072.4 2208.36
  5184.7 2209.78  5368.6 2215.24  5437.9 2220.78    5481  2225.4  5562.8 2231.76
#Mann= 5 ,-1 , 0
    4476     .07       0  4757.8     .16       0  4989.6     .07       0
  5000.1     .07       0    5022     .07       0
Bank Sta=5000.1,5022
XS Rating Curve= 0 ,0
Exp/Cntr=0.3,0.1

Type RM Length L Ch R = 1 ,9540    ,596,596,596
BEGIN DESCRIPTION:
Finn Creek 13.0
END DESCRIPTION:
XS GIS Cut Line= 3
        1364405.      6838088.03      1364518.77      6837501.15
      1365104.98      6836688.03
#Sta/Elev= 30
  4402.2 2233.83  4428.1 2230.71  4433.2 2231.63  4479.8 2222.55  4524.5 2217.58
  4588.4 2215.32  4677.3 2207.27    4718 2201.16  4738.4 2196.13  4795.3 2202.96
  4840.2  2196.7  4891.2 2195.18    4893 2192.26  4893.5 2191.76  4914.9 2192.26
  4921.7 2197.52  4950.6    2199  4955.6 2197.28  4972.7  2197.2  5006.1 2192.97
  5028.5 2193.46  5071.1  2207.7    5092 2210.04  5250.4 2207.53  5307.9 2205.08
  5343.5 2201.72  5379.1 2204.25  5601.2 2209.54  5687.1 2213.47  6002.4 2220.99
#Mann= 3 ,-1 , 0
  4402.2     .07       0    4893     .07       0  4914.9     .07       0
#XS Ineff= 2 , 0
         4788.92 2203.32 5113.26         2216.04
Permanent Ineff=
       F       F
Bank Sta=4893,4914.9
XS Rating Curve= 0 ,0
Exp/Cntr=0.3,0.1

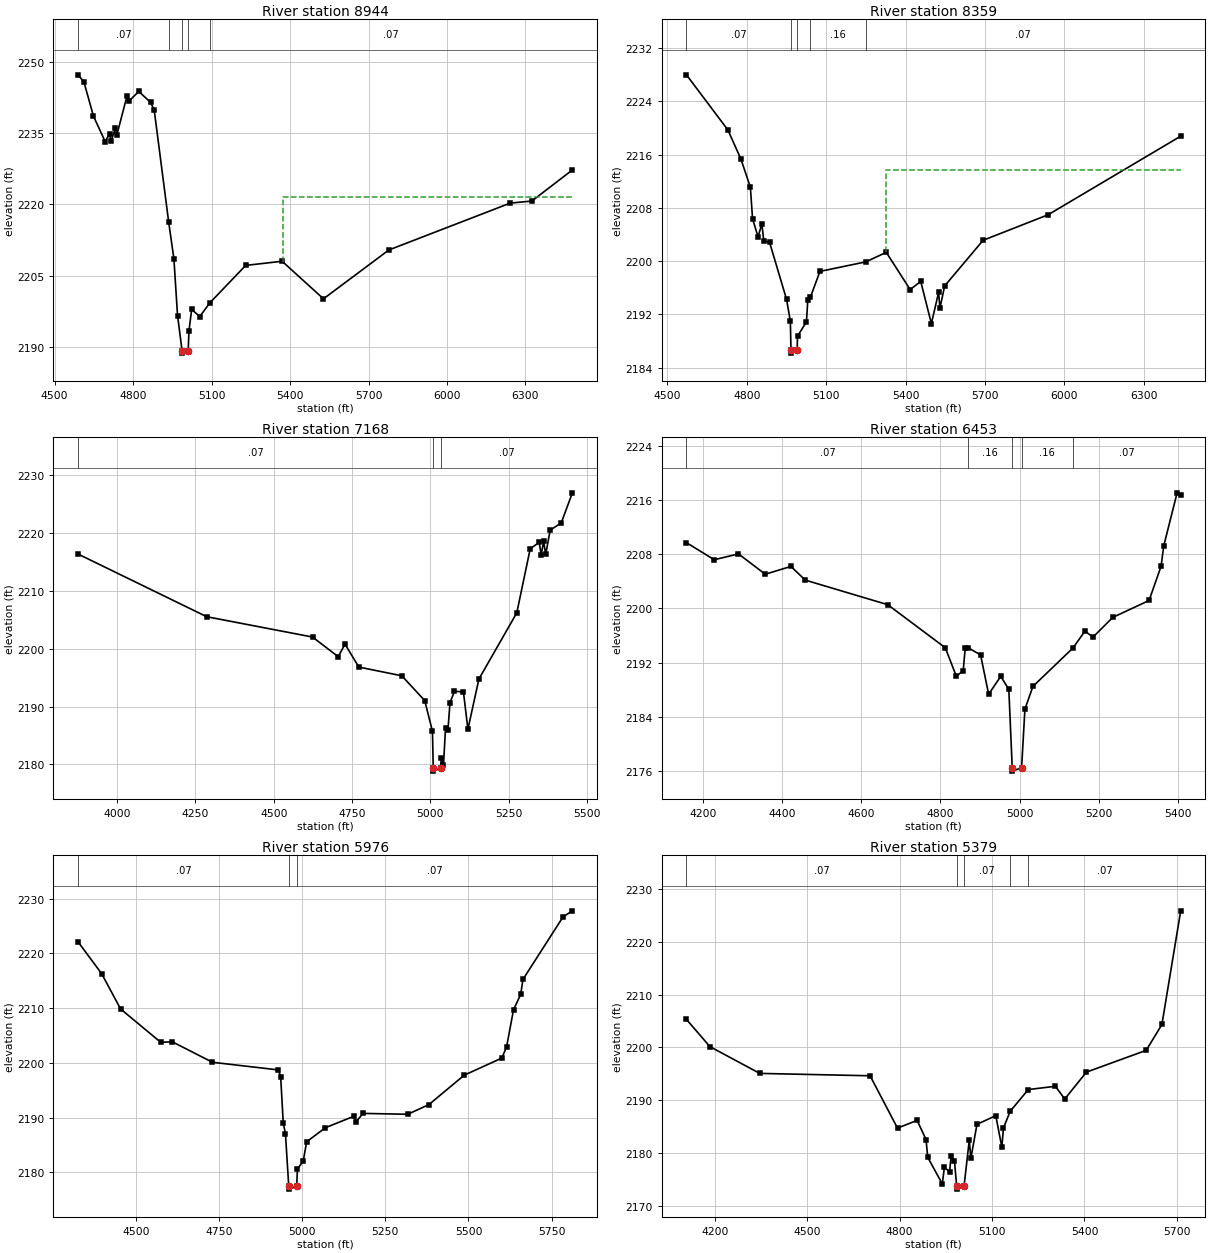
Type RM Length L Ch R = 1 ,8944    ,585,585,585
BEGIN DESCRIPTION:
Finn Creek 12.0
END DESCRIPTION:
XS GIS Cut Line= 3
      1364655.01      6838287.98       1364838.4      6837921.17
        1365205.      6836488.01
#Sta/Elev= 30
  4589.9 2247.32  4612.2 2245.79  4648.6  2238.6  4693.3 2233.25  4710.1 2234.91
  4715.7 2233.31  4732.4  2236.1    4738 2234.67  4777.1 2242.92  4782.7 2241.71
  4821.9 2243.81  4866.6 2241.52  4880.6 2239.96  4936.2 2216.22    4956 2208.54
    4970 2196.54  4987.3 2189.15  4987.8 2188.65  5010.6 2189.15  5013.6 2193.33
  5023.9 2197.86  5054.9 2196.36  5092.8 2199.21  5230.4 2207.14  5369.7 2208.02
  5527.8  2200.1  5777.9  2210.4  6241.9 2220.28  6324.5 2220.71  6479.3 2227.27
#Mann= 5 ,-1 , 0
  4589.9     .07       0  4936.2     .16       0  4987.3     .07       0
  5010.6     .16       0  5092.8     .07       0
#XS Ineff= 2 , 0
                         5373.63         2221.61
Permanent Ineff=
       F       F
Bank Sta=4987.3,5010.6
XS Rating Curve= 0 ,0
Exp/Cntr=0.3,0.1

Type RM Length L Ch R = 1 ,8359    ,1191,1191,1191
BEGIN DESCRIPTION:
Finn Creek 11.0
END DESCRIPTION:
XS GIS Cut Line= 3
      1364954.99      6838488.01      1365291.78      6838224.38
        1365205.        6836788.
#Sta/Elev= 30
  4572.3 2227.98  4728.7 2219.71  4778.5 2215.28  4813.8 2211.09  4821.9 2206.38
  4842.7 2203.66  4857.1 2205.61  4864.4 2203.03  4886.1 2202.85  4950.3 2194.28
  4964.7    2191    4967  2186.7  4967.5  2186.2  4990.3  2186.7  4991.9 2188.75
  5025.5  2190.9  5030.5 2194.11  5040.2 2194.57  5076.5 2198.47  5249.7  2199.9
    5327 2201.33  5417.1 2195.75  5457.2 2196.96  5497.3 2190.64  5524.7 2195.32
  5529.7 2192.94  5547.4 2196.28  5692.7 2203.14  5938.1 2206.97    6439 2218.77
#Mann= 5 ,-1 , 0
  4572.3     .07       0    4967     .07       0  4990.3     .07       0
  5040.2     .16       0  5249.7     .07       0
#XS Ineff= 2 , 0
                         5326.83          2213.7
Permanent Ineff=
       F       F
Bank Sta=4967,4990.3
XS Rating Curve= 0 ,0
Exp/Cntr=0.3,0.1

Type RM Length L Ch R = 1 ,7168    ,715,715,715
BEGIN DESCRIPTION:
Finn Creek 10.0
END DESCRIPTION:
XS GIS Cut Line= 3
      1365520.31      6838829.36      1365758.54      6837730.18
      1366104.99      6837438.01
#Sta/Elev= 30
  3875.3 2216.37    4286 2205.54  4623.6 2202.03  4705.5 2198.64  4727.4  2200.8
  4771.4 2196.84  4908.7 2195.33  4981.8 2191.05  5006.5 2185.74    5009 2179.35
  5009.5 2178.85  5032.6 2179.35  5034.6 2181.07  5041.7 2179.84  5048.2 2186.28
    5056    2186  5062.5 2190.68  5076.8 2192.66  5105.4 2192.54  5119.7 2186.09
  5154.8 2194.77  5275.7 2206.21  5318.6 2217.29  5347.2 2218.39  5353.7 2216.26
  5361.5 2218.57    5368  2216.3  5382.3 2220.52  5417.5 2221.74  5453.2 2226.96
#Mann= 3 ,-1 , 0
  3875.3     .07       0    5009     .07       0  5032.6     .07       0
Bank Sta=5009,5032.6
XS Rating Curve= 0 ,0
Exp/Cntr=0.3,0.1

Type RM Length L Ch R = 1 ,6453    ,477,477,477
BEGIN DESCRIPTION:
Finn Creek 9.1
END DESCRIPTION:
XS GIS Cut Line= 3
      1366069.97      6838846.92      1366237.97      6838021.44
      1366173.47      6837618.97
#Sta/Elev= 30
  4157.6 2209.71  4227.9 2207.19  4289.2 2208.05  4356.9 2205.05  4421.8  2206.2
  4458.1 2204.18  4666.7 2200.55  4812.2 2194.19  4840.2 2189.97  4857.6 2190.82
  4862.7 2194.21  4870.8 2194.17  4901.5 2193.13  4921.9 2187.33  4952.5 2189.97
  4972.9 2188.04  4981.5 2176.47    4982 2175.97  5005.2 2176.47  5013.6 2185.12
  5033.9 2188.49  5134.9 2194.14  5165.5 2196.65  5185.8 2195.76  5235.7 2198.67
  5327.6 2201.17  5357.9 2206.21  5364.7 2209.23  5398.5 2217.07  5407.6 2216.72
#Mann= 5 ,-1 , 0
  4157.6     .07       0  4870.8     .16       0  4981.5     .07       0
  5005.2     .16       0  5134.9     .07       0
Bank Sta=4981.5,5005.2
XS Rating Curve= 0 ,0
Exp/Cntr=0.3,0.1

Type RM Length L Ch R = 1 ,5976    ,597,597,597
BEGIN DESCRIPTION:
Finn Creek 9.0
END DESCRIPTION:
XS GIS Cut Line= 3
      1367104.97      6838587.96      1366664.68      6838077.25
      1366104.99      6837487.99
#Sta/Elev= 30
  4325.7 2222.11  4396.4 2216.31  4453.5 2209.85  4574.1 2203.76  4609.2 2203.84
  4729.9  2200.1  4928.5  2198.7  4935.1 2197.41  4942.8 2189.02  4949.4 2187.04
  4959.4  2177.4  4959.9  2176.9  4983.2  2177.4  4985.5  2180.6  5002.9    2182
  5013.2 2185.56  5069.8 2188.14  5154.8 2190.21    5162 2189.23  5183.1 2190.75
  5317.4 2190.59  5381.3 2192.37  5487.3 2197.74  5600.5 2200.87  5614.7  2202.9
  5635.7 2209.72  5657.2 2212.52    5664 2215.26  5784.6 2226.69  5812.7  2227.8
#Mann= 3 ,-1 , 0
  4325.7     .07       0  4959.4     .07       0  4983.2     .07       0
Bank Sta=4959.4,4983.2
XS Rating Curve= 0 ,0
Exp/Cntr=0.3,0.1

Type RM Length L Ch R = 1 ,5379    ,348,348,348
BEGIN DESCRIPTION:
Finn Creek 8.0
END DESCRIPTION:
XS GIS Cut Line= 3
      1367205.01      6838388.02      1366855.35      6837567.85
      1366154.98        6837438.
#Sta/Elev= 30
  4108.4 2205.29  4184.5 2200.14  4346.4 2195.07  4704.3 2194.62  4793.3 2184.71
  4856.9 2186.18  4885.9 2182.55  4891.4 2179.18  4938.6 2174.15  4945.5 2177.29
  4962.2 2176.44  4967.6  2179.5  4978.1 2178.56  4985.3 2173.66  4985.8 2173.16
  5009.1 2173.66  5026.2 2182.42  5031.3 2178.97  5051.2 2185.43  5112.2 2187.07
  5131.9 2181.09    5137 2184.71  5158.9 2187.89  5217.6 2192.01  5305.7 2192.63
    5336 2190.22  5406.3 2195.31  5600.4 2199.44  5651.3 2204.33  5712.3 2225.85
#Mann= 5 ,-1 , 0
  4108.4     .07       0  4985.3     .07       0  5009.1     .07       0
  5158.9     .16       0  5217.6     .07       0
Bank Sta=4985.3,5009.1
XS Rating Curve= 0 ,0
Exp/Cntr=0.3,0.1

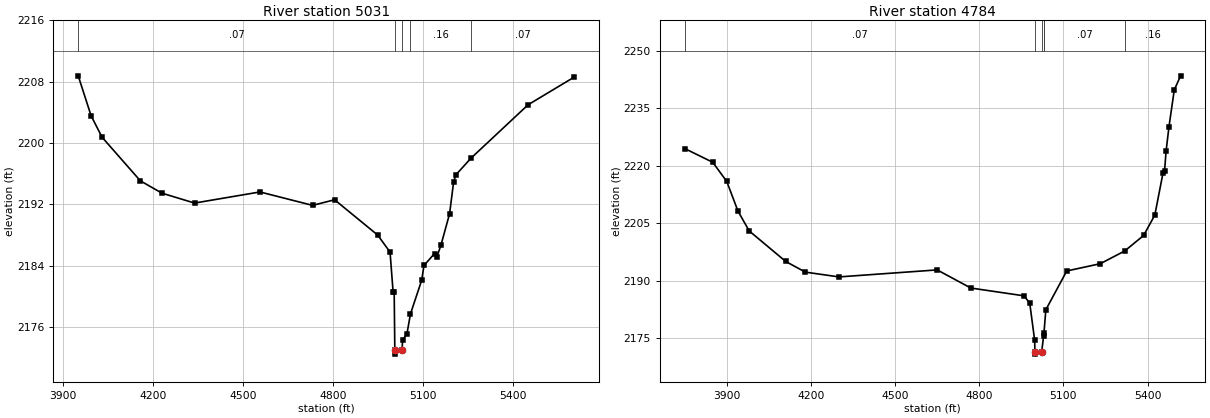
Type RM Length L Ch R = 1 ,5031    ,247,247,247
BEGIN DESCRIPTION:
Finn Creek 7.1
END DESCRIPTION:
XS GIS Cut Line= 3
      1367228.14      6838409.84      1366989.78      6837387.46
      1366586.81      6836939.42
#Sta/Elev= 30
  3950.2 2208.77  3993.2 2203.55  4029.6 2200.76  4157.3 2195.06  4229.3 2193.45
  4337.8 2192.16  4555.7 2193.61    4731 2191.86  4804.4 2192.59  4948.1 2187.98
  4989.2 2185.76  4999.5 2180.49    5003 2180.49  5005.1 2172.94  5005.6 2172.44
    5029 2172.94  5031.2 2174.31  5045.4 2175.07  5057.2 2177.69  5094.8 2182.11
  5102.2 2184.01  5137.4 2185.57  5144.9 2185.08  5159.1 2186.71  5187.5 2190.76
    5201 2194.92  5208.4 2195.84  5258.9 2198.02  5449.1 2204.99  5602.6  2208.6
#Mann= 5 ,-1 , 0
  3950.2     .07       0  5005.1     .07       0    5029     .07       0
  5057.2     .16       0  5258.9     .07       0
Bank Sta=5005.1,5029
XS Rating Curve= 0 ,0
Exp/Cntr=0.3,0.1

Type RM Length L Ch R = 1 ,4784    ,559,559,559
BEGIN DESCRIPTION:
Finn Creek 7.0
END DESCRIPTION:
XS GIS Cut Line= 3
        1367255.      6838587.98      1367220.02      6837337.97
      1367355.01      6836837.97
#Sta/Elev= 30
  3749.5 2224.54  3849.5 2220.95  3899.5 2215.96  3939.6  2208.2  3979.6 2203.04
  4109.6 2195.09  4179.7  2192.3  4299.7 2191.05  4649.8 2192.88  4769.9 2188.15
    4960 2186.11    4980 2184.16  4997.5 2174.49  4998.4 2171.41  4998.9 2170.91
  5022.3 2171.41  5029.2 2175.54  5030.6 2176.38  5037.3 2182.48  5111.9  2192.6
  5231.6  2194.5  5318.4 2197.81    5386 2201.86  5425.9 2207.18  5455.4 2218.27
  5460.6 2218.61  5466.1 2223.87  5476.4 2230.23  5495.3 2239.84  5517.9  2243.5
#Mann= 6 ,-1 , 0
  3749.5     .07       0  4998.4     .07       0  5022.3     .07       0
  5029.2     .16       0  5030.6     .07       0  5318.4     .16       0
Bank Sta=4998.4,5022.3
XS Rating Curve= 0 ,0
Exp/Cntr=0.3,0.1