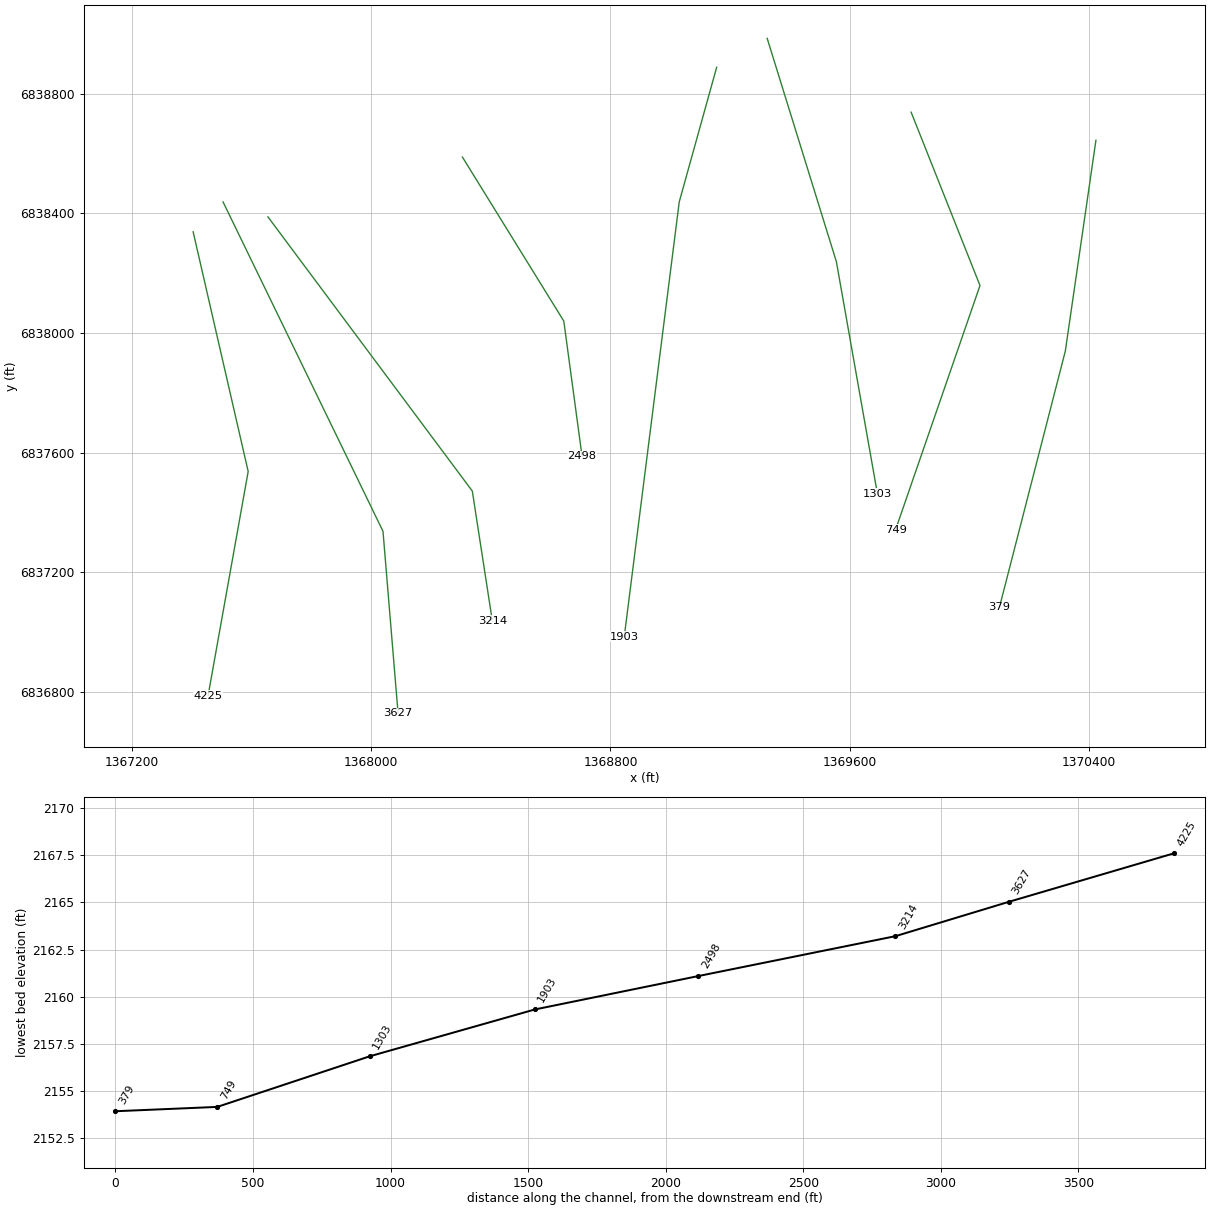
HEC-RAS study Finn Creek.prj: Finn Creek Base Level Engineering

--- Finn Creek.g01 (geometry) --- (continued)

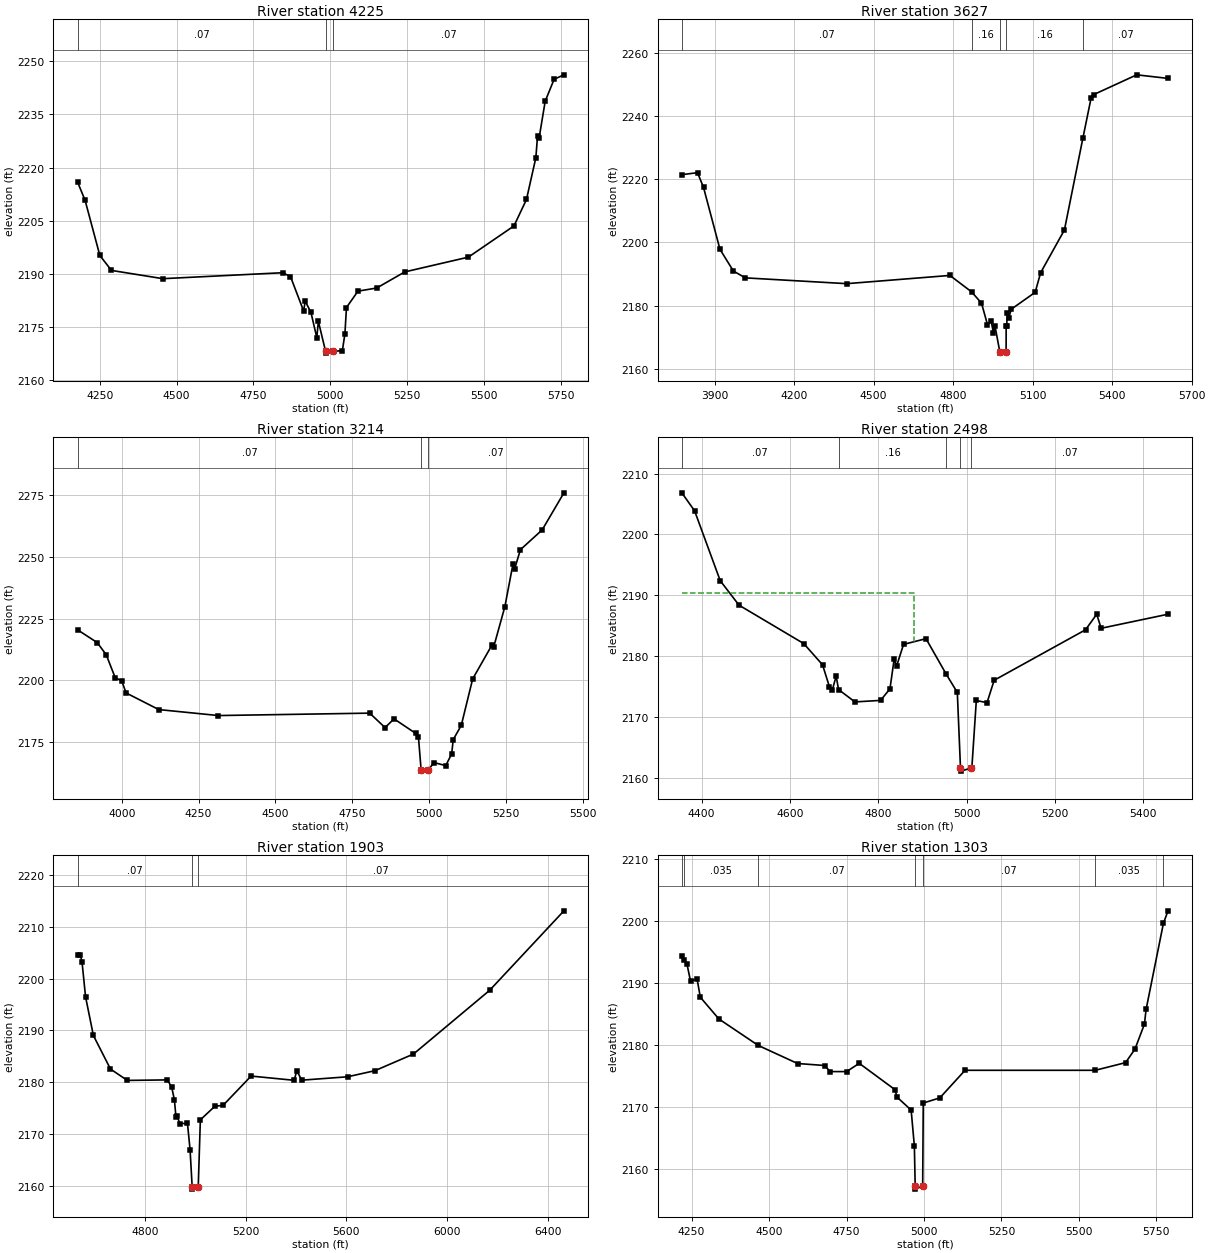
Type RM Length L Ch R = 1 ,4225    ,598,598,598
BEGIN DESCRIPTION:
Finn Creek 6.0
END DESCRIPTION:
XS GIS Cut Line= 3
      1367404.99      6838338.04      1367588.98       6837536.9
        1367455.      6836787.99
#Sta/Elev= 30
    4178  2215.8    4202 2210.74    4250 2195.18  4287.8 2190.96  4455.1 2188.63
    4845 2190.31  4870.6 2189.23  4913.4 2179.51  4918.6 2182.29  4937.3 2179.09
  4956.3 2171.98  4961.4 2176.58  4984.9 2168.11  4985.4 2167.61  5008.8 2168.11
  5039.5  2168.3  5047.8 2173.04  5052.9 2180.49  5090.3 2185.11  5151.3 2185.99
  5242.7 2190.54  5449.7 2194.71  5598.2 2203.52  5638.9    2211  5669.4 2222.78
    5675 2228.99  5680.1 2228.39  5699.8 2238.72  5728.8 2244.92  5760.8 2246.18
#Mann= 3 ,-1 , 0
    4178     .07       0  4984.9     .07       0  5008.8     .07       0
Bank Sta=4984.9,5008.8
XS Rating Curve= 0 ,0
Exp/Cntr=0.3,0.1

Type RM Length L Ch R = 1 ,3627    ,413,413,413
BEGIN DESCRIPTION:
Finn Creek 5.0
END DESCRIPTION:
XS GIS Cut Line= 3
        1367505.      6838438.01       1368039.6      6837337.04
      1368090.02      6836728.33
#Sta/Elev= 30
  3776.1 2221.43  3835.3 2222.06  3857.9 2217.42    3920 2197.84  3970.7 2190.98
  4015.8 2188.82  4398.6 2186.99  4787.7 2189.59  4869.2 2184.42  4906.9 2180.85
  4929.5 2174.04  4943.4 2175.12    4952 2171.46  4957.6 2173.71  4975.8 2165.54
  4976.3 2165.04  4999.8 2165.54    5000 2173.69    5002 2173.69  5004.4  2177.8
  5009.4    2176  5019.1 2178.91  5109.4 2184.25  5130.2 2190.47  5219.8 2203.95
  5289.5 2232.97  5320.1  2245.5  5330.2 2246.73  5492.6 2252.98  5610.8 2251.85
#Mann= 5 ,-1 , 0
  3776.1     .07       0  4869.2     .16       0  4975.8     .07       0
  4999.8     .16       0  5289.5     .07       0
Bank Sta=4975.8,4999.8
XS Rating Curve= 0 ,0
Exp/Cntr=0.3,0.1

Type RM Length L Ch R = 1 ,3214    ,716,716,716
BEGIN DESCRIPTION:
Finn Creek 4.0
END DESCRIPTION:
XS GIS Cut Line= 3
      1367655.01      6838387.99       1368338.2      6837471.39
        1368405.      6837038.01
#Sta/Elev= 30
  3856.8 2220.43  3920.4 2215.28  3949.6 2210.34  3978.8 2201.03  3999.6 2199.86
  4014.2 2194.89  4120.5 2188.15  4314.5 2185.73  4806.6 2186.71  4856.6 2180.85
  4885.8 2184.39  4956.7 2178.47  4965.1 2177.24  4973.9 2163.71  4974.4 2163.21
  4997.9 2163.71  5015.2 2166.68    5054 2165.46  5073.3 2170.18  5078.4 2175.99
  5104.6 2181.77  5141.6 2200.57  5204.7 2214.37  5209.8 2213.42  5246.3 2229.82
    5273 2247.26    5278 2245.06  5296.9 2252.94  5367.7 2260.95  5438.5 2275.98
#Mann= 3 ,-1 , 0
  3856.8     .07       0  4973.9     .07       0  4997.9     .07       0
Bank Sta=4973.9,4997.9
XS Rating Curve= 0 ,0
Exp/Cntr=0.3,0.1

Type RM Length L Ch R = 1 ,2498    ,595,595,595
BEGIN DESCRIPTION:
Finn Creek 3.0
END DESCRIPTION:
XS GIS Cut Line= 3
      1368305.01      6838587.98      1368643.98      6838039.71
        1368705.      6837588.01
#Sta/Elev= 30
  4355.4 2206.85  4384.3 2203.89  4442.3  2192.4  4484.8 2188.38  4631.4 2182.06
  4673.9 2178.57  4689.3 2174.99  4696.3 2174.51  4704.7 2176.71  4710.1  2174.5
  4747.2 2172.47  4805.1 2172.72  4826.4 2174.61  4835.9 2179.45  4841.8 2178.43
  4857.2 2181.93    4908 2182.87  4954.2 2176.98  4978.9 2174.03  4986.1 2161.59
  4986.6 2161.09  5010.1 2161.59  5011.8 2161.63  5021.9 2172.71  5046.1 2172.34
  5062.3 2176.03  5269.1 2184.33  5294.4 2186.89  5304.4 2184.58  5455.8 2186.89
#Mann= 5 ,-1 , 0
  4355.4     .07       0  4710.1     .16       0  4954.2     .07       0
  4986.1     .07       0  5010.1     .07       0
#XS Ineff= 2 , 0
         4880.34 2190.42
Permanent Ineff=
       F       F
Bank Sta=4986.1,5010.1
XS Rating Curve= 0 ,0
Exp/Cntr=0.3,0.1

Type RM Length L Ch R = 1 ,1903    ,600,600,600
BEGIN DESCRIPTION:
Finn Creek 2.0
END DESCRIPTION:
XS GIS Cut Line= 3
      1369154.99      6838887.97      1369029.92      6838438.24
      1368846.16      6836985.01
#Sta/Elev= 30
  4533.2 2204.63  4543.5 2204.57  4550.3 2203.22  4564.3  2196.5  4595.4 2189.02
  4663.4 2182.52  4730.4 2180.33  4889.5 2180.43  4906.8 2178.98  4917.2 2176.59
  4923.7 2173.19  4928.9 2173.54    4938 2171.95  4969.1 2172.06  4979.5 2166.95
  4987.8 2159.81  4988.3 2159.31    5012 2159.81  5020.4 2172.71  5077.5 2175.31
  5111.1 2175.53    5222 2181.17  5393.1 2180.35  5403.4 2182.18  5423.6 2180.38
    5605 2181.03  5713.8 2182.21  5867.1 2185.43  6169.5 2197.74  6464.8 2213.12
#Mann= 3 ,-1 , 0
  4533.2     .07       0  4987.8     .07       0    5012     .07       0
Bank Sta=4987.8,5012
XS Rating Curve= 0 ,0
Exp/Cntr=0.3,0.1

Type RM Length L Ch R = 1 ,1303    ,554,554,554
BEGIN DESCRIPTION:
Finn Creek 1.0
END DESCRIPTION:
XS GIS Cut Line= 3
      1369323.82      6838984.81      1369555.14      6838238.33
      1369692.26      6837462.96
#Sta/Elev= 30
  4218.5 2194.28  4225.7 2193.77  4235.1 2193.05  4246.6 2190.29  4267.5 2190.71
  4278.2 2187.71  4338.1 2184.21  4465.1 2179.95    4592 2177.04  4679.8 2176.72
  4696.7 2175.74  4750.2 2175.74    4791 2177.07  4906.1 2172.84  4913.2 2171.62
  4958.5 2169.54  4968.9 2163.73  4971.5 2157.32    4972 2156.82  4995.7 2157.32
  4997.6 2170.68  5051.1 2171.51  5132.4 2175.95  5552.5 2175.95  5650.3 2177.18
  5680.7 2179.36  5711.2 2183.37  5716.6 2185.74  5772.5 2199.61  5787.4 2201.62
#Mann= 7 ,-1 , 0
  4218.5     .07       0  4225.7    .035       0  4465.1     .07       0
  4971.5     .07       0  4995.7     .07       0  5552.5    .035       0
  5772.5     .07       0
Bank Sta=4971.5,4995.7
XS Rating Curve= 0 ,0
Exp/Cntr=0.3,0.1

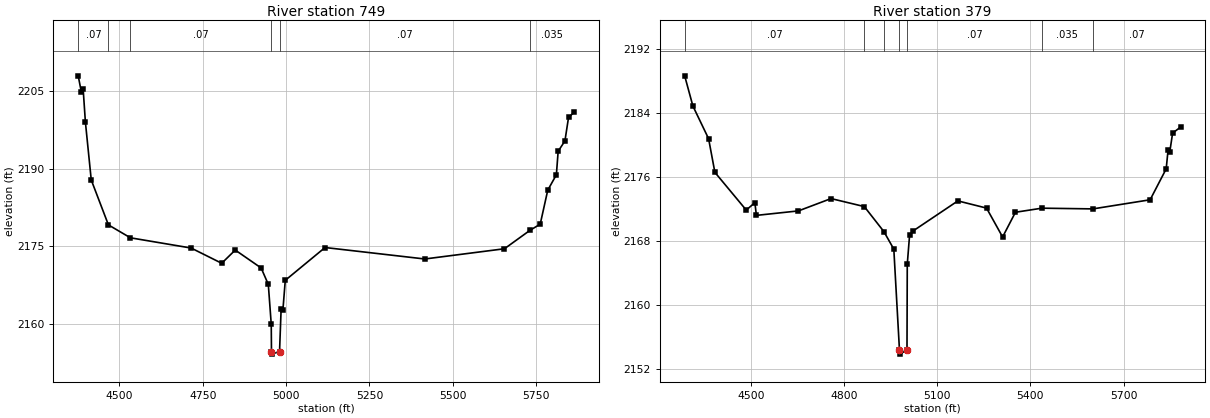
Type RM Length L Ch R = 1 ,749     ,370,370,370
BEGIN DESCRIPTION:
Finn Creek 0.2
END DESCRIPTION:
XS GIS Cut Line= 3
      1369805.02      6838737.96       1370035.2       6838158.5
      1369752.88      6837341.82
#Sta/Elev= 30
  4376.5 2208.01  4385.9 2204.87  4391.3 2205.48    4398 2199.09  4415.6 2187.85
  4467.1 2179.15  4533.1 2176.65  4715.2 2174.67  4806.9 2171.72  4847.5 2174.28
  4925.2 2170.81  4946.7 2167.63  4955.5 2159.93  4956.2 2154.63  4956.7 2154.13
  4980.4 2154.63  4985.2 2162.95  4990.5 2162.69  4997.6 2168.42  5116.9 2174.77
  5416.1 2172.55    5655 2174.53  5731.4 2178.09  5762.3 2179.29  5784.9 2185.87
  5810.8 2188.86  5816.1 2193.41  5836.4  2195.4  5847.3 2199.97  5864.1 2200.95
#Mann= 6 ,-1 , 0
  4376.5     .07       0  4467.1     .16       0  4533.1     .07       0
  4956.2     .07       0  4980.4     .07       0  5731.4    .035       0
Bank Sta=4956.2,4980.4
XS Rating Curve= 0 ,0
Exp/Cntr=0.3,0.1

Type RM Length L Ch R = 1 ,379     ,0,0,0
BEGIN DESCRIPTION:
Finn Creek 0.1
END DESCRIPTION:
XS GIS Cut Line= 3
      1370422.81      6838644.17      1370320.36      6837938.88
      1370100.22      6837083.03
#Sta/Elev= 30
  4287.3 2188.68  4313.7 2184.91  4364.3 2180.82  4384.5 2176.62  4485.5  2171.9
  4513.2 2172.83  4518.2 2171.24  4653.5  2171.8  4758.4 2173.34  4865.5 2172.34
  4928.6 2169.21  4960.5 2167.02  4978.7  2154.4  4979.2  2153.9  5002.9  2154.4
  5003.8 2165.13  5011.2 2168.74  5021.6 2169.27  5166.7 2173.05    5259 2172.15
  5310.7 2168.54    5352 2171.63  5437.1 2172.14  5601.3 2172.05  5785.6 2173.19
  5837.3 2177.06  5843.4 2179.45  5848.6 2179.12  5857.9 2181.52  5883.7 2182.28
#Mann= 7 ,-1 , 0
  4287.3     .07       0  4865.5     .16       0  4928.6     .07       0
  4978.7     .07       0  5002.9     .07       0  5437.1    .035       0
  5601.3     .07       0
Bank Sta=4978.7,5002.9
XS Rating Curve= 0 ,0
Exp/Cntr=0.3,0.1

Chan Stop Cuts=-1
Use User Specified Reach Order=0
Composite Channel Slope=5