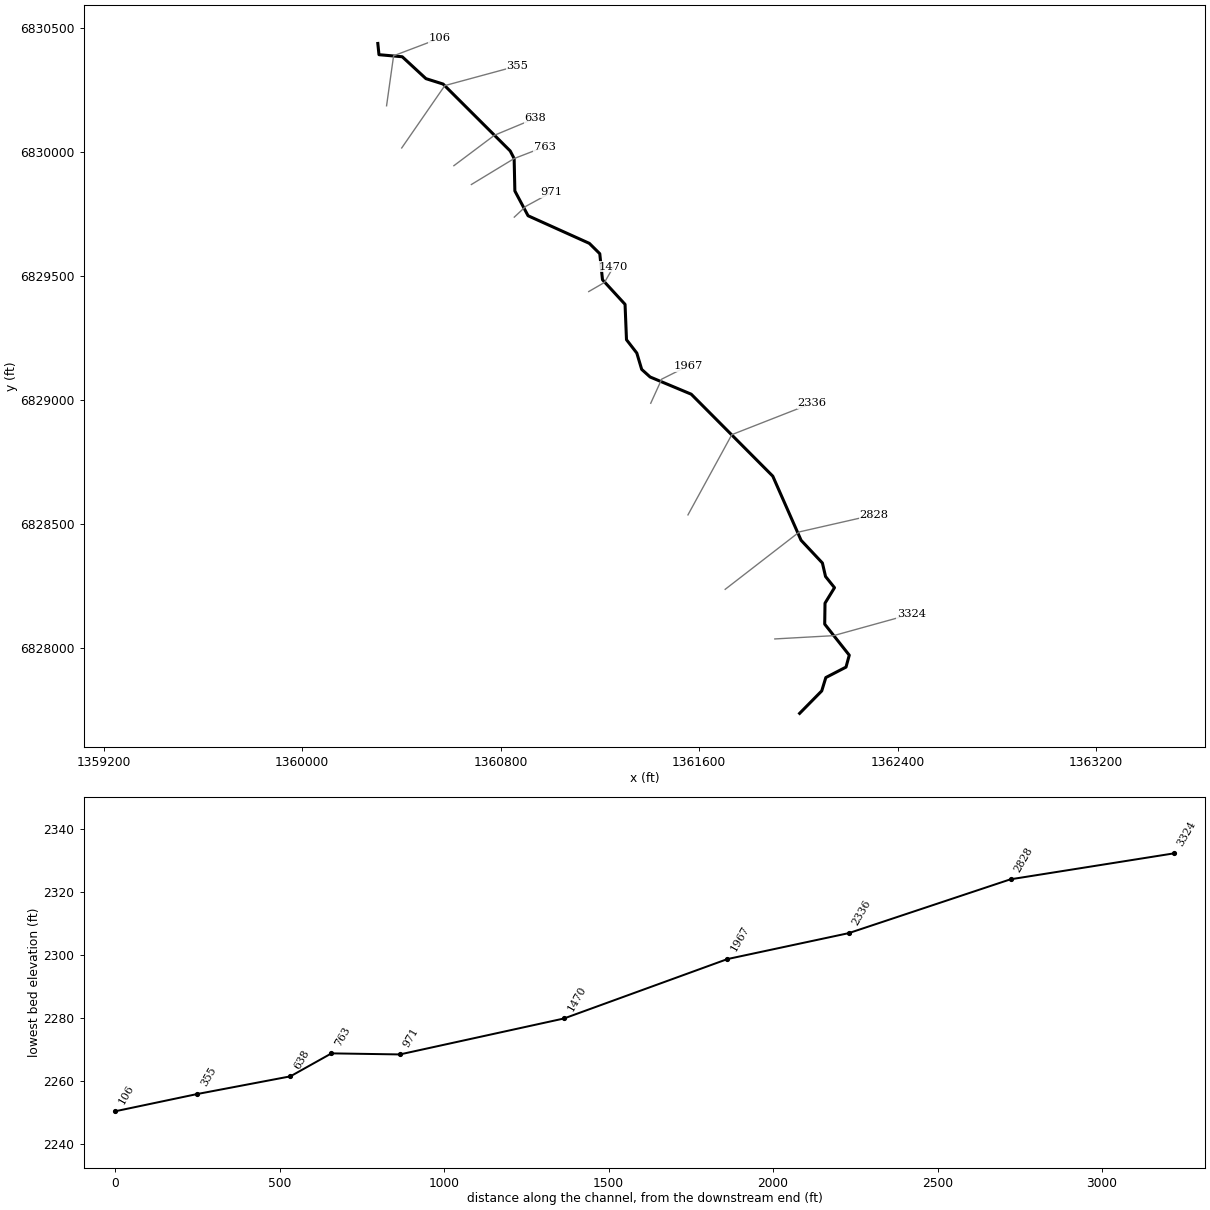
--- Finn Creek Trib1.prj (project) ---

Proj Title=Finn Creek Trib1 Base Level Engineering
Current Plan=p01
Default Exp/Contr=0.3,0.1
English Units
Geom File=g01
Flow File=f01
Plan File=p01
Y Axis Title=Elevation
X Axis Title(PF)=Main Channel Distance
X Axis Title(XS)=Station
BEGIN DESCRIPTION:
Finn Creek Trib1
END DESCRIPTION:
DSS Export Rating Curves= 0
DSS Export Rating Curve Sorted= 0
DSS Export Volume Flow Curves= 0
DXF OffsetX= 0
DXF OffsetY= 0
DXF ScaleX= 1
DXF ScaleY= 10

--- Finn Creek Trib1.p01 (plan) ---

Plan Title=Multiple Run
Short Identifier=Multiple
Geom File=g01
Flow File=f01
Subcritical Flow
K Sum by GR= 0
Std Step Tol= 0.01
Critical Tol= 0.01
Num of Std Step Trials= 20
Max Error Tol= 0.3
Flow Tol Ratio= 0.001
Split Flow NTrial= 30
Split Flow Tol= 0.02
Split Flow Ratio= 0.02
Log Output Level= 0
Friction Slope Method= 1
Unsteady Friction Slope Method= 2
Unsteady Bridges Friction Slope Method= 1
Parabolic Critical Depth
Global Vel Dist=  1 , 1 , 1
Global Log Level= 0
CheckData=True
Encroach Param= -1, 0, 0, 0
BEGIN DESCRIPTION:
Multiple Run
END DESCRIPTION:

--- Finn Creek Trib1.f01 (steady flow) ---

Flow Title=Multiple
Number of Profiles=7
Profile Names=10-year,25-year,50-year,1pct_min,100-year,1pct_plu,500-year
River Rch & RM= Finn Creek Trib1,Reach-1,3324
     186     261     323     200     399     795     613
Boundary for River Rch & Prof#=Finn Creek Trib1,Reach-1,1
Up Type=0
Dn Type=3
Dn Slope=0.005
Boundary for River Rch & Prof#=Finn Creek Trib1,Reach-1,2
Up Type=0
Dn Type=3
Dn Slope=0.005
Boundary for River Rch & Prof#=Finn Creek Trib1,Reach-1,3
Up Type=0
Dn Type=3
Dn Slope=0.005
Boundary for River Rch & Prof#=Finn Creek Trib1,Reach-1,4
Up Type=0
Dn Type=3
Dn Slope=0.005
Boundary for River Rch & Prof#=Finn Creek Trib1,Reach-1,5
Up Type=0
Dn Type=3
Dn Slope=0.005
Boundary for River Rch & Prof#=Finn Creek Trib1,Reach-1,6
Up Type=0
Dn Type=3
Dn Slope=0.005
Boundary for River Rch & Prof#=Finn Creek Trib1,Reach-1,7
Up Type=0
Dn Type=3
Dn Slope=0.005

--- Finn Creek Trib1.g01 (geometry) ---

Geom Title=Existing Conditions

River Reach=Finn Creek Trib1,Reach-1
Reach XY= 30
      1362005.00      6827738.00      1362094.17      6827828.58
      1362110.64      6827882.38      1362191.97      6827924.47
      1362205.12      6827972.58      1362106.11      6828097.64
      1362107.36      6828182.10      1362145.59      6828244.62
      1362109.45      6828289.65      1362096.86      6828344.04
      1362010.85      6828435.71      1361896.86      6828694.06
      1361568.21      6829024.38      1361402.45      6829093.73
      1361368.47      6829124.43      1361348.85      6829190.15
      1361307.25      6829243.93      1361301.44      6829386.53
      1361210.54      6829485.58      1361199.58      6829590.67
      1361157.58      6829632.28      1360910.58      6829743.58
      1360857.35      6829843.50      1360854.45      6829974.14
      1360838.57      6830004.76      1360568.21      6830274.37
      1360498.96      6830296.18      1360403.47      6830384.42
      1360309.68      6830392.75      1360305.00      6830438.00

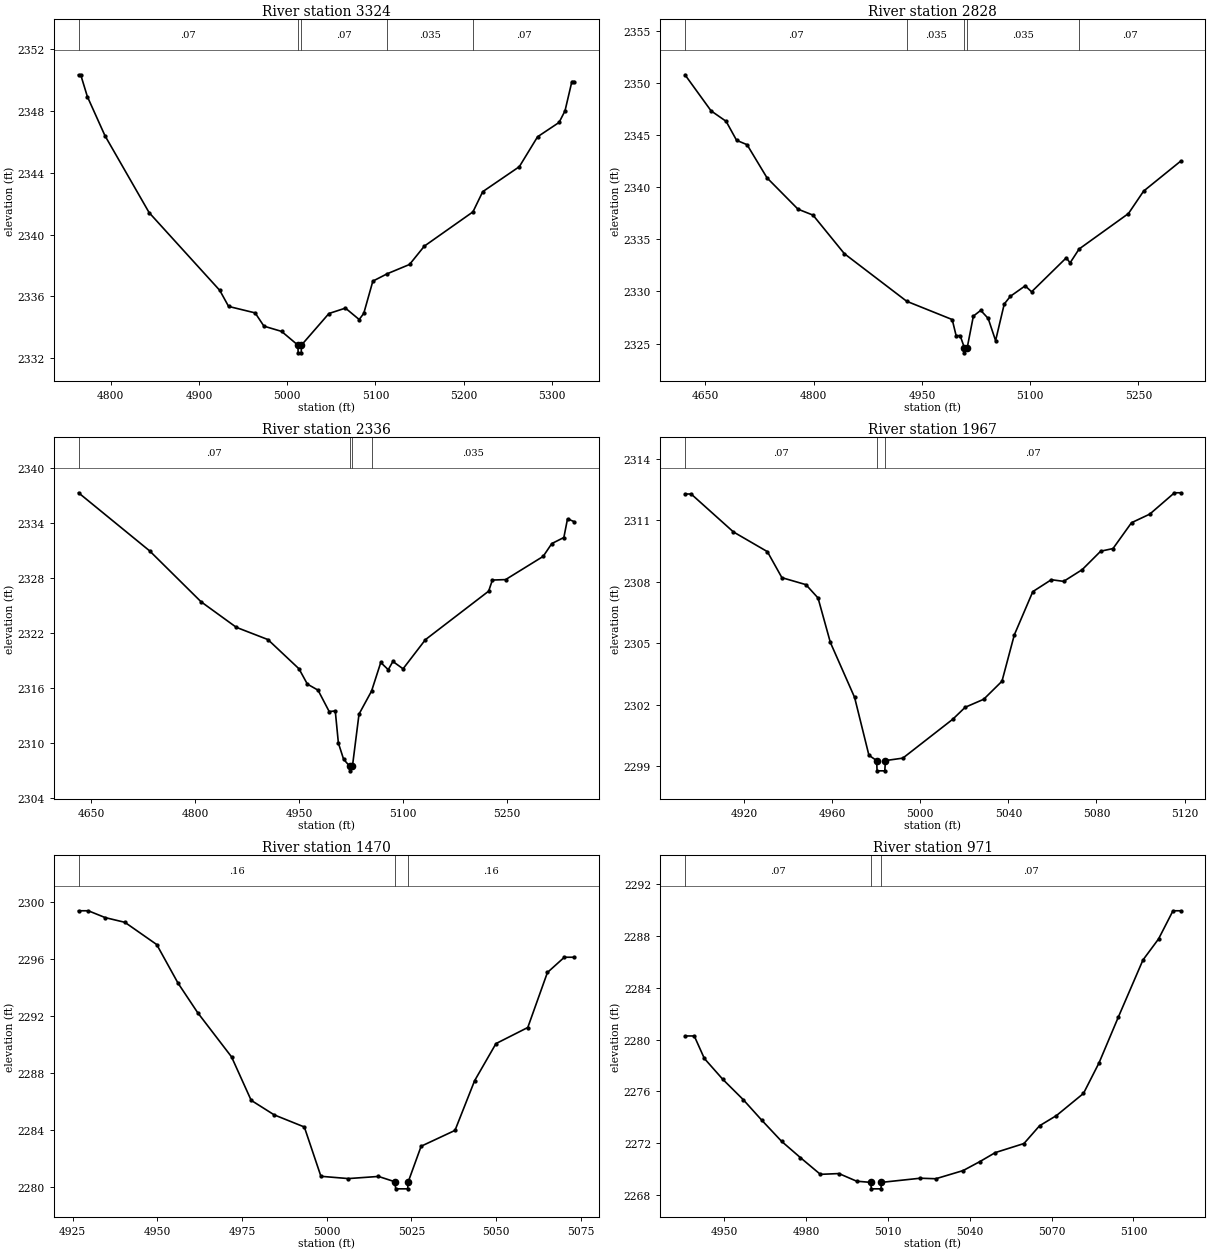
Type RM Length L Ch R = 1,3324,496,496,496
BEGIN DESCRIPTION:
Finn Creek Trib1 6.0
END DESCRIPTION:
XS GIS Cut Line= 3
      1361905.04      6828038.00      1362141.37      6828051.21
      1362454.98      6828138.00
#Sta/Elev= 30
  4763.3 2350.36  4765.8 2350.36  4773.3 2348.95  4793.3 2346.41  4843.4 2341.42
  4923.5 2336.38  4933.5 2335.34  4963.6 2334.92  4973.6 2334.06  4993.6 2333.72
  5012.1 2332.83  5012.4 2332.33  5015.9 2332.33  5016.1 2332.83  5047.3 2334.88
  5066.0 2335.23  5081.6 2334.49  5086.8 2334.89  5097.1 2336.98  5113.5 2337.46
  5138.7 2338.06  5155.5 2339.25  5210.6 2341.47  5221.7 2342.78  5263.2 2344.40
  5283.9 2346.34  5308.3 2347.27  5315.0 2348.02  5322.8 2349.92  5325.4 2349.92
#Mann=5,-1,0
  4763.3    0.07       0  5012.1    0.07       0  5016.1    0.07       0
  5113.5   0.035       0  5210.6    0.07       0
Bank Sta=5012.1,5016.1
Exp/Cntr=0.3,0.1

Type RM Length L Ch R = 1,2828,492,492,492
BEGIN DESCRIPTION:
Finn Creek Trib1 5.0
END DESCRIPTION:
XS GIS Cut Line= 3
      1361705.03      6828238.03      1362004.34      6828469.55
      1362305.05      6828538.01
#Sta/Elev= 30
  4621.6 2350.76  4657.8 2347.30  4678.6 2346.30  4693.1 2344.48  4707.6 2344.06
  4735.3 2340.88  4778.2 2337.88  4799.0 2337.31  4842.5 2333.61  4928.9 2329.05
  4991.9 2327.30  4997.3 2325.76  5002.9 2325.76  5008.7 2324.61  5008.9 2324.11
  5012.7 2324.61  5021.2 2327.63  5031.4 2328.18  5041.7 2327.41  5052.0 2325.28
  5064.0 2328.79  5072.5 2329.53  5093.0 2330.53  5101.9 2329.96  5150.0 2333.22
  5155.2 2332.73  5167.7 2334.06  5236.1 2337.46  5257.1 2339.61  5308.4 2342.48
#Mann=5,-1,0
  4621.6    0.07       0  4928.9   0.035       0  5008.7   0.035       0
  5012.7   0.035       0  5167.7    0.07       0
Bank Sta=5008.7,5012.7
Exp/Cntr=0.3,0.1

Type RM Length L Ch R = 1,2336,369,369,369
BEGIN DESCRIPTION:
Finn Creek Trib1 4.0
END DESCRIPTION:
XS GIS Cut Line= 3
      1361554.98      6828537.96      1361731.67      6828861.33
      1362055.04      6828988.01
#Sta/Elev= 30
  4631.5 2337.34  4734.1 2331.01  4808.5 2325.45  4859.5 2322.66  4905.0 2321.33
  4949.9 2318.14  4962.0 2316.47  4977.4 2315.81  4993.5 2313.48  5002.3 2313.54
  5006.8 2310.04  5014.3 2308.28  5023.1 2307.51  5023.3 2307.01  5027.1 2307.51
  5036.6 2313.20  5054.7 2315.71  5068.0 2318.83  5078.8 2318.04  5085.5 2318.94
  5100.2 2318.14  5132.5 2321.32  5223.8 2326.61  5229.2 2327.82  5248.3 2327.87
  5302.5 2330.40  5315.0 2331.80  5332.4 2332.46  5337.7 2334.50  5347.3 2334.19
#Mann=4,-1,0
  4631.5    0.07       0  5023.1    0.07       0  5027.1    0.07       0
  5054.7   0.035       0
Bank Sta=5023.1,5027.1
Exp/Cntr=0.3,0.1

Type RM Length L Ch R = 1,1967,497,497,497
BEGIN DESCRIPTION:
Finn Creek Trib1 3.0
END DESCRIPTION:
XS GIS Cut Line= 3
      1361404.98      6828987.96      1361449.25      6829085.16
      1361554.98      6829137.99
#Sta/Elev= 30
  4893.2 2312.27  4896.0 2312.27  4915.2 2310.42  4930.6 2309.46  4937.2 2308.19
  4948.1 2307.85  4953.6 2307.20  4959.2 2305.03  4970.2 2302.35  4976.7 2299.53
  4980.2 2299.27  4980.4 2298.77  4983.9 2298.77  4984.2 2299.27  4992.1 2299.39
  5014.8 2301.29  5020.4 2301.87  5028.8 2302.26  5037.1 2303.14  5042.7 2305.40
  5051.1 2307.51  5059.5 2308.09  5065.1 2308.01  5073.5 2308.58  5081.9 2309.48
  5087.5 2309.61  5095.9 2310.87  5104.2 2311.29  5115.4 2312.33  5118.2 2312.33
#Mann=3,-1,0
  4893.2    0.07       0  4980.2    0.07       0  4984.2    0.07       0
Bank Sta=4980.2,4984.2
Exp/Cntr=0.3,0.1

Type RM Length L Ch R = 1,1470,499,499,499
BEGIN DESCRIPTION:
Finn Creek Trib1 2.0
END DESCRIPTION:
XS GIS Cut Line= 3
      1361154.99      6829438.00      1361218.43      6829474.71
      1361255.00      6829538.01
#Sta/Elev= 26
  4926.7 2299.41  4929.6 2299.41  4934.6 2298.93  4940.4 2298.60  4949.8 2297.04
  4956.1 2294.33  4961.9 2292.26  4971.9 2289.16  4977.7 2286.11  4984.5 2285.09
  4993.4 2284.24  4998.3 2280.78  5006.4 2280.62  5015.3 2280.77  5020.1 2280.40
  5020.4 2279.90  5023.9 2279.90  5024.1 2280.40  5027.9 2282.89  5037.9 2284.00
  5043.7 2287.49  5050.0 2290.09  5059.4 2291.22  5065.2 2295.08  5070.2 2296.15
  5073.1 2296.15
#Mann=3,-1,0
  4926.7    0.16       0  5020.1    0.07       0  5024.1    0.16       0
Bank Sta=5020.1,5024.1
Exp/Cntr=0.3,0.1

Type RM Length L Ch R = 1,971,208,208,208
BEGIN DESCRIPTION:
Finn Creek Trib1 1.0
END DESCRIPTION:
XS GIS Cut Line= 3
      1360855.00      6829738.00      1360901.99      6829781.89
      1361005.00      6829838.00
#Sta/Elev= 30
  4935.7 2280.29  4939.1 2280.29  4942.8 2278.55  4949.6 2276.93  4957.0 2275.38
  4963.8 2273.79  4971.1 2272.15  4978.0 2270.89  4985.3 2269.60  4992.1 2269.66
  4998.6 2269.07  5003.7 2268.98  5004.0 2268.48  5007.5 2268.48  5007.7 2268.98
  5021.9 2269.30  5027.6 2269.26  5037.6 2269.89  5043.7 2270.58  5049.4 2271.28
  5059.9 2271.98  5065.6 2273.35  5071.8 2274.14  5081.7 2275.85  5087.4 2278.21
  5094.5 2281.76  5103.5 2286.16  5109.2 2287.78  5114.5 2289.96  5117.3 2289.96
#Mann=3,-1,0
  4935.7    0.07       0  5003.7    0.07       0  5007.7    0.07       0
Bank Sta=5003.7,5007.7
Exp/Cntr=0.3,0.1

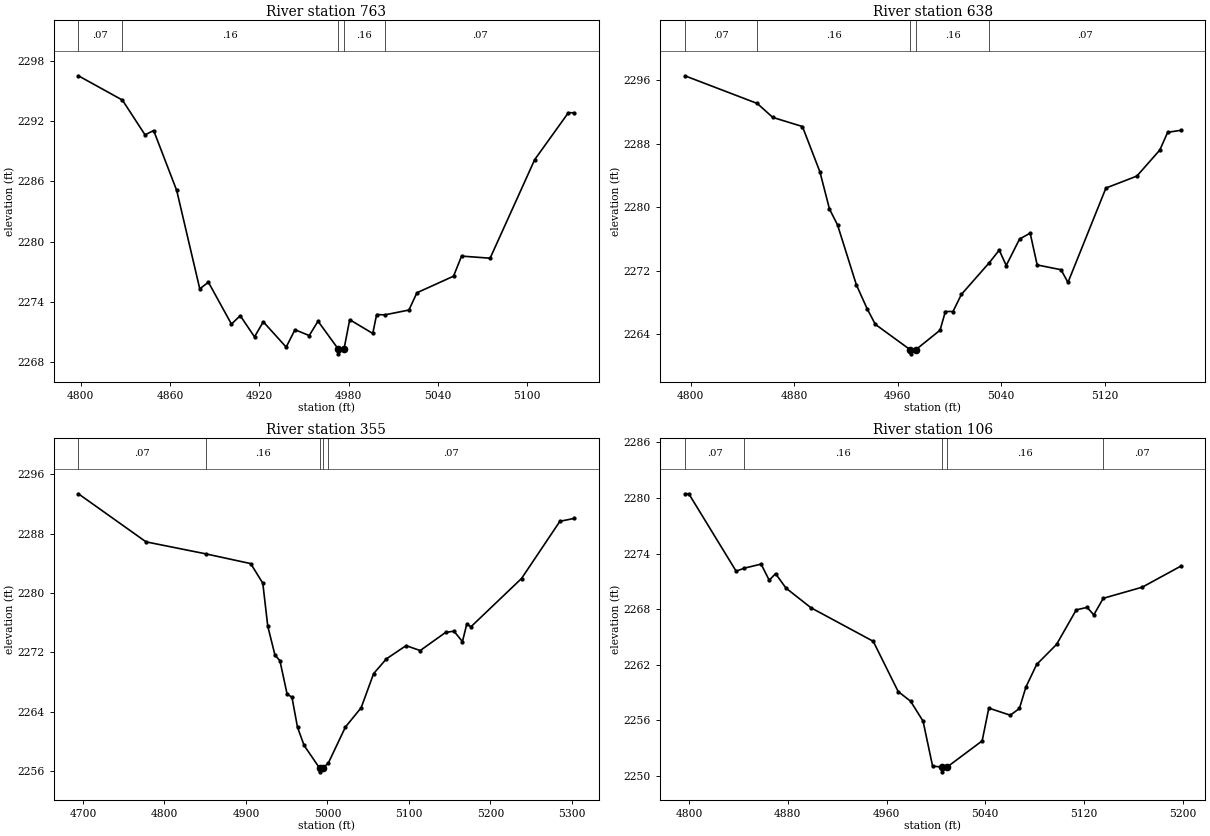
Type RM Length L Ch R = 1,763,125,125,125
BEGIN DESCRIPTION:
Finn Creek Trib1 0.3
END DESCRIPTION:
XS GIS Cut Line= 3
      1360682.11      6829869.53      1360854.45      6829974.14
      1360977.31      6830021.56
#Sta/Elev= 30
  4798.4 2296.50  4828.0 2294.08  4843.2 2290.62  4849.0 2291.05  4864.5 2285.08
  4880.0 2275.29  4885.8 2275.95  4901.3 2271.78  4907.2 2272.62  4916.8 2270.51
  4922.7 2272.01  4938.1 2269.49  4944.0 2271.22  4953.6 2270.64  4959.5 2272.07
  4973.0 2269.32  4973.2 2268.82  4977.0 2269.32  4980.8 2272.22  4996.3 2270.85
  4998.9 2272.73  5004.4 2272.70  5020.6 2273.18  5026.0 2274.90  5050.6 2276.55
  5056.0 2278.55  5075.2 2278.34  5105.2 2288.16  5127.8 2292.82  5131.7 2292.82
#Mann=5,-1,0
  4798.4    0.07       0  4828.0    0.16       0  4973.0    0.07       0
  4977.0    0.16       0  5004.4    0.07       0
Bank Sta=4973,4977
Exp/Cntr=0.3,0.1

Type RM Length L Ch R = 1,638,283,283,283
BEGIN DESCRIPTION:
Finn Creek Trib1 0.2
END DESCRIPTION:
XS GIS Cut Line= 3
      1360611.56      6829945.33      1360775.04      6830068.02
      1360939.85      6830136.57
#Sta/Elev= 30
  4795.6 2296.59  4851.5 2293.10  4863.5 2291.34  4886.4 2290.19  4899.9 2284.48
  4907.3 2279.78  4913.5 2277.79  4928.1 2270.21  4936.4 2267.20  4942.7 2265.24
  4969.8 2262.02  4970.1 2261.52  4973.8 2262.02  4992.7 2264.50  4996.8 2266.86
  5002.7 2266.86  5009.2 2269.02  5030.8 2273.03  5038.4 2274.60  5043.8 2272.66
  5054.1 2276.00  5062.3 2276.74  5067.7 2272.73  5086.1 2272.13  5091.5 2270.53
  5120.8 2282.43  5144.7 2283.94  5162.4 2287.22  5168.5 2289.46  5178.5 2289.71
#Mann=5,-1,0
  4795.6    0.07       0  4851.5    0.16       0  4969.8    0.07       0
  4973.8    0.16       0  5030.8    0.07       0
Bank Sta=4969.8,4973.8
Exp/Cntr=0.3,0.1

Type RM Length L Ch R = 1,355,249,249,249
BEGIN DESCRIPTION:
Finn Creek Trib1 0.1
END DESCRIPTION:
XS GIS Cut Line= 3
      1360401.33      6830016.82      1360575.09      6830268.21
      1360867.34      6830347.43
#Sta/Elev= 30
  4694.4 2293.39  4777.4 2286.91  4850.4 2285.30  4905.8 2283.98  4920.7 2281.34
  4926.8 2275.54  4935.6 2271.66  4941.7 2270.89  4950.5 2266.41  4956.5 2265.95
  4963.3 2261.91  4971.4 2259.47  4990.4 2256.41  4990.6 2255.91  4994.4 2256.41
  5001.2 2257.11  5022.1 2261.95  5041.4 2264.55  5056.7 2269.15  5072.4 2271.14
  5096.5 2272.92  5113.9 2272.26  5145.0 2274.70  5155.3 2274.87  5165.7 2273.46
  5171.0 2275.82  5176.2 2275.47  5238.2 2281.97  5285.3 2289.68  5302.8 2290.07
#Mann=5,-1,0
  4694.4    0.07       0  4850.4    0.16       0  4990.4    0.07       0
  4994.4    0.16       0  5001.2    0.07       0
Bank Sta=4990.4,4994.4
Exp/Cntr=0.3,0.1

Type RM Length L Ch R = 1,106,0,0,0
BEGIN DESCRIPTION:
Finn Creek Trib1 4318
END DESCRIPTION:
XS GIS Cut Line= 3
      1360340.26      6830186.78      1360368.59      6830388.29
      1360554.10      6830458.64
#Sta/Elev= 30
  4796.5 2280.45  4799.7 2280.45  4838.1 2272.09  4844.6 2272.42  4858.3 2272.86
  4864.9 2271.12  4870.0 2271.83  4878.5 2270.27  4898.7 2268.15  4949.2 2264.53
  4969.4 2259.11  4979.5 2258.06  4989.6 2255.91  4997.3 2251.07  5004.9 2250.94
  5005.1 2250.44  5008.9 2250.94  5037.5 2253.78  5042.9 2257.32  5060.3 2256.55
  5067.7 2257.28  5073.0 2259.60  5081.7 2262.03  5097.8 2264.19  5113.8 2267.92
  5122.6 2268.19  5128.0 2267.38  5135.7 2269.17  5167.3 2270.37  5198.4 2272.63
#Mann=5,-1,0
  4796.5    0.07       0  4844.6    0.16       0  5004.9    0.07       0
  5008.9    0.16       0  5135.7    0.07       0
Bank Sta=5004.9,5008.9
Exp/Cntr=0.3,0.1

Chan Stop Cuts=-1