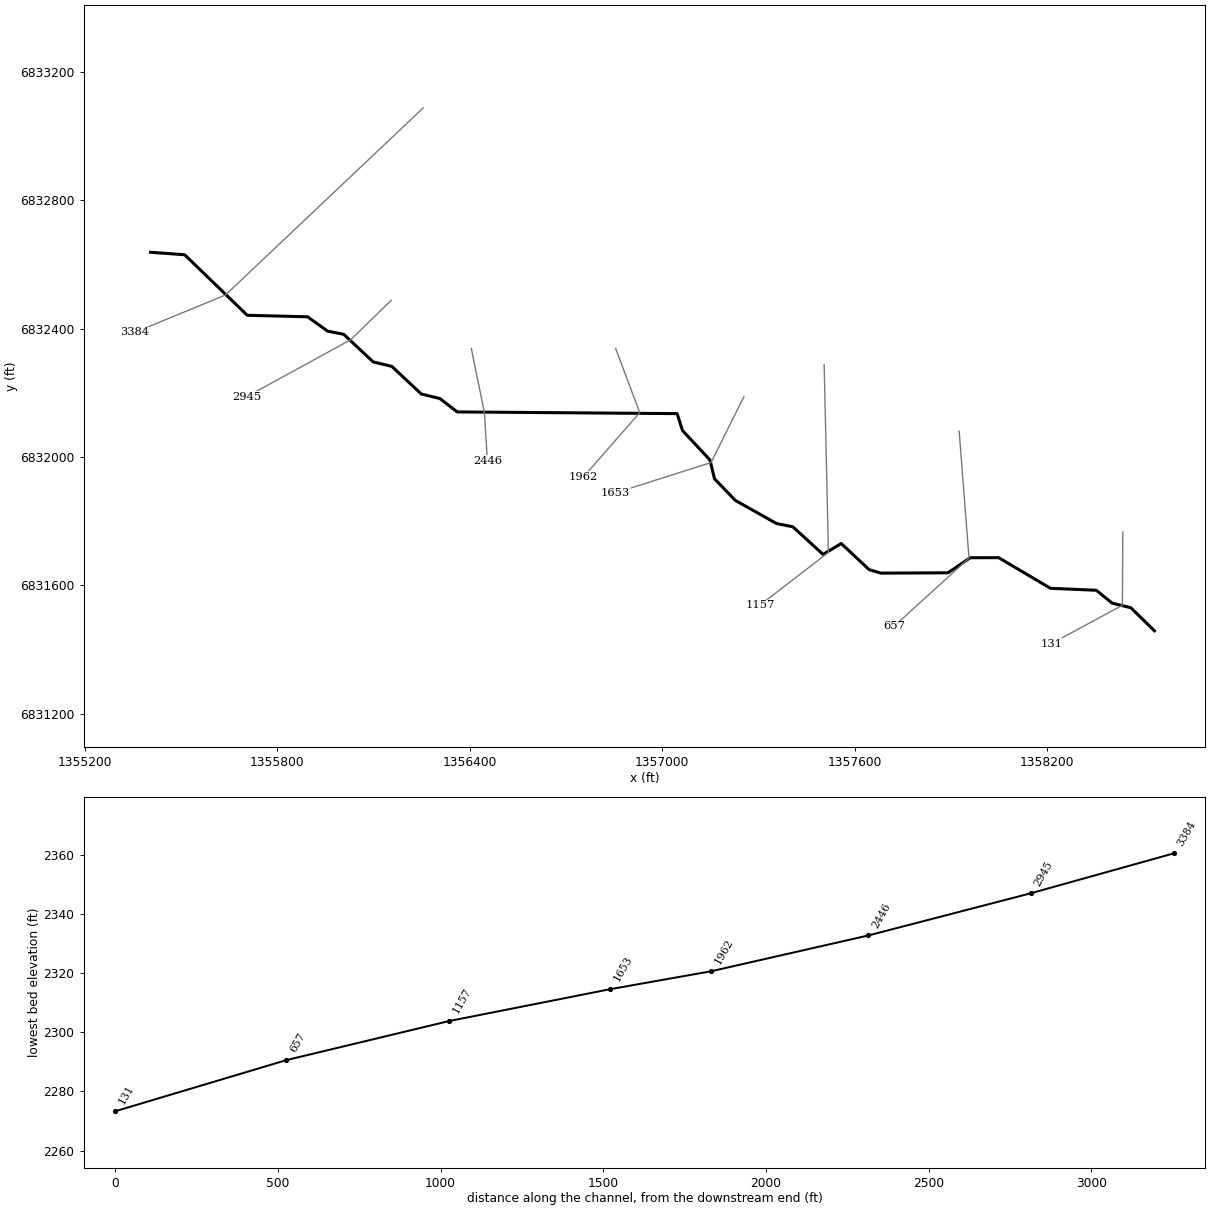
--- Finn Creek Trib2.prj (project) ---

Proj Title=Finn Creek Trib2 Base Level Engineering
Current Plan=p01
Default Exp/Contr=0.3,0.1
English Units
Geom File=g01
Flow File=f01
Plan File=p01
BEGIN DESCRIPTION:
Finn Creek Trib2
END DESCRIPTION:

--- Finn Creek Trib2.p01 (plan) ---

Plan Title=Multiple Run
Short Identifier=Multiple
Geom File=g01
Flow File=f01
Subcritical Flow
K Sum by GR= 0
Std Step Tol= 0.01
Critical Tol= 0.01
Num of Std Step Trials= 20
Max Error Tol= 0.3
Flow Tol Ratio= 0.001
Split Flow NTrial= 30
Split Flow Tol= 0.02
Split Flow Ratio= 0.02
Log Output Level= 0
Friction Slope Method= 1
Unsteady Friction Slope Method= 2
Unsteady Bridges Friction Slope Method= 1
Parabolic Critical Depth
Global Vel Dist=  1 , 1 , 1
Global Log Level= 0
CheckData=True
Encroach Param= -1, 0, 0, 0
BEGIN DESCRIPTION:
Multiple Run
END DESCRIPTION:

--- Finn Creek Trib2.f01 (steady flow) ---

Flow Title=Multiple
Number of Profiles=7
Profile Names=10-year,25-year,50-year,1pct_min,100-year,1pct_plu,500-year
River Rch & RM= Finn Creek Trib2,Reach-1,3384
      67      88     104      62     124     247     175
Boundary for River Rch & Prof#=Finn Creek Trib2,Reach-1,1
Up Type=0
Dn Type=3
Dn Slope=0.005
Boundary for River Rch & Prof#=Finn Creek Trib2,Reach-1,2
Up Type=0
Dn Type=3
Dn Slope=0.005
Boundary for River Rch & Prof#=Finn Creek Trib2,Reach-1,3
Up Type=0
Dn Type=3
Dn Slope=0.005
Boundary for River Rch & Prof#=Finn Creek Trib2,Reach-1,4
Up Type=0
Dn Type=3
Dn Slope=0.005
Boundary for River Rch & Prof#=Finn Creek Trib2,Reach-1,5
Up Type=0
Dn Type=3
Dn Slope=0.005
Boundary for River Rch & Prof#=Finn Creek Trib2,Reach-1,6
Up Type=0
Dn Type=3
Dn Slope=0.005
Boundary for River Rch & Prof#=Finn Creek Trib2,Reach-1,7
Up Type=0
Dn Type=3
Dn Slope=0.005

--- Finn Creek Trib2.g01 (geometry) ---

Geom Title=Existing Conditions

River Reach=Finn Creek Trib2,Reach-1
Reach XY= 30
      1355405.00      6832638.00      1355511.22      6832630.26
      1355706.46      6832441.54      1355894.50      6832436.80
      1355956.75      6832392.22      1356007.29      6832382.16
      1356098.96      6832296.18      1356157.28      6832282.13
      1356248.95      6832196.16      1356307.17      6832181.86
      1356360.93      6832140.24      1357046.70      6832134.93
      1357063.32      6832082.31      1357149.13      6831990.28
      1357163.15      6831931.93      1357228.12      6831864.27
      1357356.74      6831792.19      1357407.30      6831782.14
      1357501.67      6831696.02      1357558.33      6831729.98
      1357645.20      6831648.52      1357682.12      6831637.64
      1357891.08      6831638.69      1357960.57      6831685.71
      1358049.03      6831685.86      1358210.52      6831590.36
      1358353.44      6831584.24      1358402.83      6831544.14
      1358461.05      6831529.84      1358534.68      6831457.87

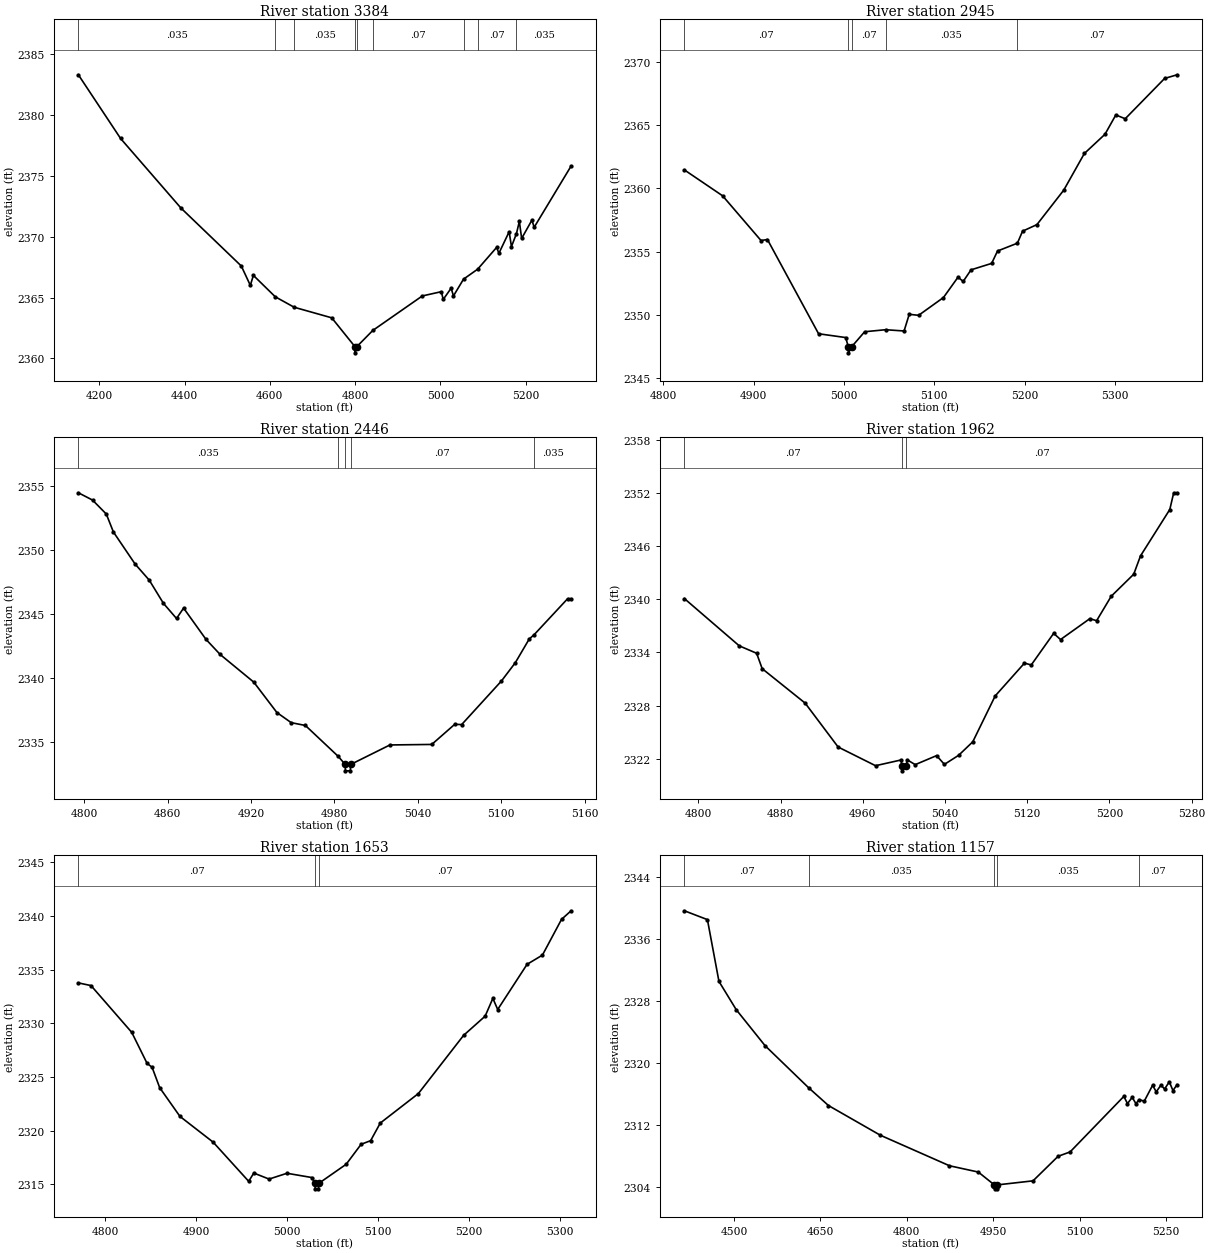
Type RM Length L Ch R = 1,3384,439,439,439
BEGIN DESCRIPTION:
Finn Creek Trib2 10.0
END DESCRIPTION:
XS GIS Cut Line= 3
      1356255.03      6833088.03      1355638.29      6832504.57
      1355355.03      6832388.01
#Sta/Elev= 30
  4151.0 2383.33  4250.0 2378.09  4391.5 2372.37  4533.1 2367.60  4554.2 2366.01
  4561.4 2366.83  4612.7 2365.07  4657.0 2364.21  4745.1 2363.34  4799.7 2360.96
  4800.0 2360.46  4803.7 2360.96  4841.3 2362.30  4957.5 2365.14  5002.1 2365.49
  5006.5 2364.85  5025.1 2365.78  5030.5 2365.14  5054.1 2366.52  5087.2 2367.34
  5131.7 2369.13  5137.1 2368.65  5161.1 2370.42  5166.5 2369.20  5178.2 2370.26
  5185.0 2371.27  5190.4 2369.87  5214.4 2371.37  5219.8 2370.79  5306.3 2375.82
#Mann=9,-1,0
  4151.0   0.035       0  4612.7    0.07       0  4657.0   0.035       0
  4799.7    0.07       0  4803.7   0.035       0  4841.3    0.07       0
  5054.1   0.035       0  5087.2    0.07       0  5178.2   0.035       0
Bank Sta=4799.7,4803.7
Exp/Cntr=0.3,0.1

Type RM Length L Ch R = 1,2945,499,499,499
BEGIN DESCRIPTION:
Finn Creek Trib2 9.0
END DESCRIPTION:
XS GIS Cut Line= 3
      1356154.99      6832487.99      1356028.45      6832364.94
      1355704.98      6832187.99
#Sta/Elev= 30
  4823.5 2361.47  4865.8 2359.42  4908.3 2355.88  4915.4 2355.96  4972.0 2348.50
  5002.0 2348.20  5004.8 2347.49  5005.1 2346.99  5008.8 2347.49  5023.0 2348.66
  5046.1 2348.82  5066.6 2348.72  5072.3 2350.04  5082.7 2349.96  5110.2 2351.37
  5126.3 2352.98  5132.0 2352.64  5140.7 2353.56  5163.5 2354.07  5170.0 2355.05
  5192.0 2355.67  5197.7 2356.62  5213.6 2357.14  5243.3 2359.87  5266.1 2362.77
  5288.9 2364.29  5300.9 2365.82  5311.3 2365.52  5354.9 2368.71  5368.7 2369.00
#Mann=5,-1,0
  4823.5    0.07       0  5004.8    0.07       0  5008.8    0.07       0
  5046.1   0.035       0  5192.0    0.07       0
Bank Sta=5004.8,5008.8
Exp/Cntr=0.3,0.1

Type RM Length L Ch R = 1,2446,484,484,484
BEGIN DESCRIPTION:
Finn Creek Trib2 8.0
END DESCRIPTION:
XS GIS Cut Line= 3
      1356405.01      6832337.96      1356445.86      6832137.89
      1356455.00      6831987.97
#Sta/Elev= 30
  4795.8 2354.44  4806.0 2353.87  4815.9 2352.78  4821.0 2351.38  4836.6 2348.88
  4846.8 2347.62  4857.0 2345.81  4866.4 2344.63  4871.5 2345.44  4887.6 2343.00
  4897.8 2341.82  4922.0 2339.66  4938.6 2337.29  4948.9 2336.50  4959.1 2336.28
  4982.8 2333.86  4987.7 2333.24  4987.9 2332.74  4991.4 2332.74  4991.7 2333.24
  5019.9 2334.76  5050.0 2334.80  5066.5 2336.37  5071.5 2336.35  5100.1 2339.75
  5110.1 2341.18  5120.1 2343.03  5123.5 2343.35  5147.7 2346.17  5150.2 2346.17
#Mann=5,-1,0
  4795.8   0.035       0  4982.8    0.07       0  4987.7    0.07       0
  4991.7    0.07       0  5123.5   0.035       0
Bank Sta=4987.7,4991.7
Exp/Cntr=0.3,0.1

Type RM Length L Ch R = 1,1962,309,309,309
BEGIN DESCRIPTION:
Finn Creek Trib2 7.0
END DESCRIPTION:
XS GIS Cut Line= 3
      1356854.99      6832338.02      1356930.03      6832138.04
      1356755.00      6831938.00
#Sta/Elev= 30
  4786.4 2340.08  4839.8 2334.74  4856.7 2333.90  4862.1 2332.16  4903.9 2328.27
  4936.0 2323.31  4972.4 2321.20  4997.3 2321.85  4998.0 2321.12  4998.2 2320.62
  5002.0 2321.12  5003.4 2321.85  5011.0 2321.32  5031.8 2322.34  5039.4 2321.35
  5053.2 2322.37  5067.0 2323.90  5088.8 2329.08  5117.3 2332.79  5123.9 2332.58
  5145.7 2336.15  5152.4 2335.45  5180.9 2337.81  5187.5 2337.58  5201.7 2340.34
  5223.6 2342.83  5230.2 2344.90  5258.7 2350.14  5262.5 2352.03  5265.8 2352.03
#Mann=3,-1,0
  4786.4    0.07       0  4998.0    0.07       0  5002.0    0.07       0
Bank Sta=4998,5002
Exp/Cntr=0.3,0.1

Type RM Length L Ch R = 1,1653,496,496,496
BEGIN DESCRIPTION:
Finn Creek Trib2 6.0
END DESCRIPTION:
XS GIS Cut Line= 3
      1357254.98      6832187.96      1357152.35      6831982.35
      1356854.96      6831887.99
#Sta/Elev= 30
  4770.2 2333.78  4784.1 2333.53  4828.9 2329.17  4845.7 2326.29  4851.3 2325.91
  4859.6 2324.02  4881.9 2321.34  4918.4 2318.94  4957.5 2315.29  4963.1 2316.06
  4979.9 2315.50  4999.6 2316.04  5027.2 2315.64  5030.4 2315.09  5030.7 2314.59
  5034.2 2314.59  5034.4 2315.09  5064.7 2316.88  5081.1 2318.74  5091.6 2319.08
  5102.2 2320.72  5144.1 2323.47  5193.8 2328.89  5217.5 2330.68  5226.0 2332.34
  5231.3 2331.30  5263.6 2335.51  5280.5 2336.37  5301.5 2339.70  5312.0 2340.50
#Mann=3,-1,0
  4770.2    0.07       0  5030.4    0.07       0  5034.4    0.07       0
Bank Sta=5030.4,5034.4
Exp/Cntr=0.3,0.1

Type RM Length L Ch R = 1,1157,500,500,500
BEGIN DESCRIPTION:
Finn Creek Trib2 5.0
END DESCRIPTION:
XS GIS Cut Line= 3
      1357505.00      6832288.01      1357518.33      6831702.26
      1357305.03      6831538.03
#Sta/Elev= 30
  4414.1 2339.59  4454.1 2338.45  4474.1 2330.50  4504.1 2326.86  4554.1 2322.23
  4629.6 2316.82  4664.2 2314.52  4754.2 2310.70  4874.2 2306.77  4924.2 2305.96
  4952.2 2304.30  4952.5 2303.80  4956.0 2303.80  4956.2 2304.30  5019.2 2304.83
  5062.7 2307.99  5083.5 2308.55  5176.8 2315.70  5183.1 2314.77  5191.3 2315.58
  5197.7 2314.77  5203.4 2315.28  5212.2 2315.08  5226.7 2317.13  5233.0 2316.29
  5241.2 2317.15  5247.5 2316.65  5255.7 2317.58  5262.0 2316.45  5269.2 2317.21
#Mann=5,-1,0
  4414.1    0.07       0  4629.6   0.035       0  4952.2   0.035       0
  4956.2   0.035       0  5203.4    0.07       0
Bank Sta=4952.2,4956.2
Exp/Cntr=0.3,0.1

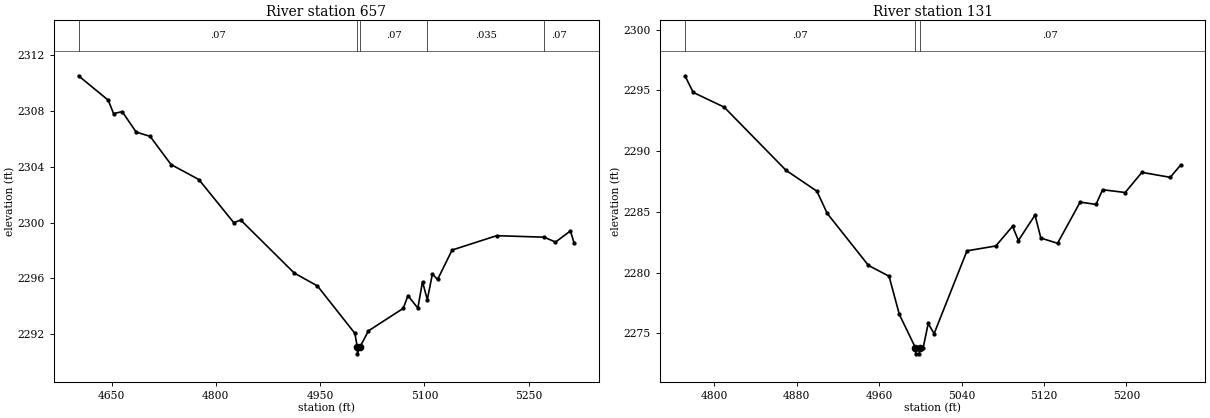
Type RM Length L Ch R = 1,657,526,526,526
BEGIN DESCRIPTION:
Finn Creek Trib2 4.0
END DESCRIPTION:
XS GIS Cut Line= 3
      1357925.92      6832080.71      1357956.60      6831684.30
      1357723.03      6831472.20
#Sta/Elev= 30
  4602.4 2310.53  4645.2 2308.78  4652.8 2307.82  4665.3 2307.96  4685.4 2306.49
  4705.4 2306.19  4735.5 2304.17  4775.6 2303.09  4825.8 2300.00  4835.8 2300.19
  4912.8 2296.39  4946.1 2295.47  5000.0 2292.07  5003.4 2291.10  5003.7 2290.60
  5007.4 2291.10  5019.6 2292.25  5069.6 2293.86  5076.4 2294.77  5090.6 2293.88
  5097.3 2295.77  5104.2 2294.48  5111.5 2296.32  5119.0 2295.93  5139.9 2298.04
  5204.1 2299.07  5272.4 2298.96  5288.6 2298.61  5310.2 2299.41  5315.5 2298.51
#Mann=5,-1,0
  4602.4    0.07       0  5003.4    0.07       0  5007.4    0.07       0
  5104.2   0.035       0  5272.4    0.07       0
Bank Sta=5003.4,5007.4
Exp/Cntr=0.3,0.1

Type RM Length L Ch R = 1,131,0,0,0
BEGIN DESCRIPTION:
Finn Creek Trib2 3.0
END DESCRIPTION:
XS GIS Cut Line= 3
      1358436.04      6831765.98      1358434.87      6831537.68
      1358212.78      6831417.34
#Sta/Elev= 30
  4771.7 2296.21  4779.7 2294.84  4809.7 2293.63  4869.7 2288.43  4899.7 2286.71
  4909.7 2284.88  4949.7 2280.60  4969.7 2279.71  4979.7 2276.56  4995.3 2273.82
  4995.6 2273.32  4999.1 2273.32  4999.3 2273.82  5002.8 2273.82  5007.7 2275.82
  5013.4 2274.98  5045.3 2281.80  5073.3 2282.20  5089.5 2283.82  5095.2 2282.65
  5111.3 2284.74  5117.0 2282.85  5133.2 2282.42  5155.1 2285.81  5170.5 2285.62
  5176.9 2286.83  5198.8 2286.60  5215.0 2288.26  5242.5 2287.85  5252.6 2288.86
#Mann=3,-1,0
  4771.7    0.07       0  4995.3    0.07       0  4999.3    0.07       0
Bank Sta=4995.3,4999.3
Exp/Cntr=0.3,0.1

Chan Stop Cuts=-1