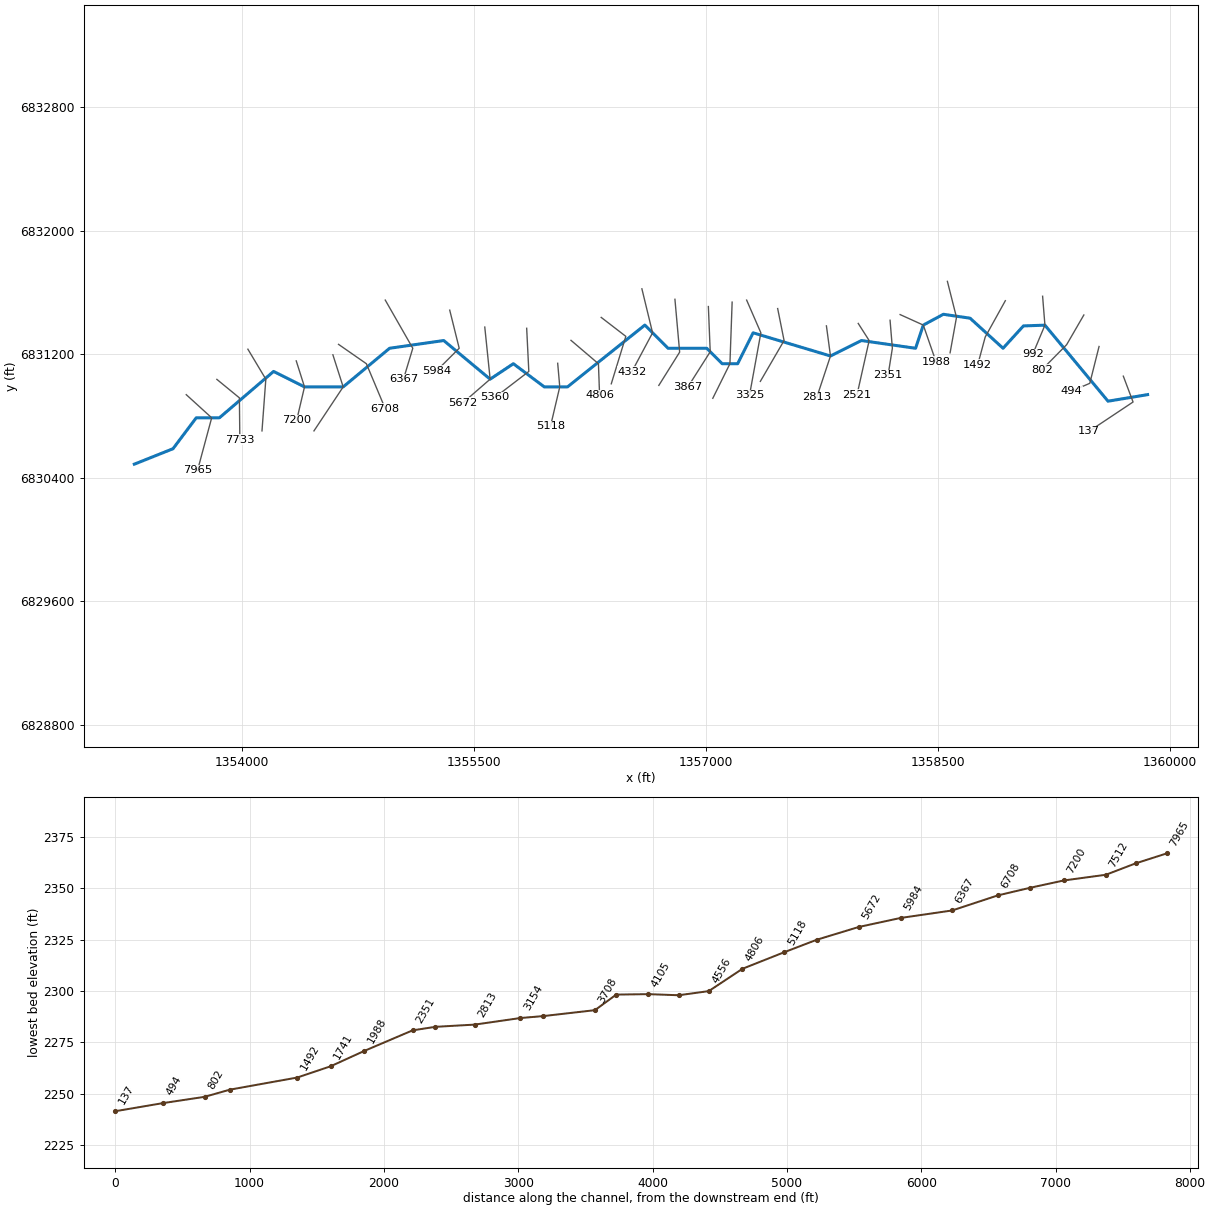
--- Finn Creek Trib2T.prj (project) ---

Proj Title=Finn Creek Trib2T Base Level Engineering
Current Plan=p01
Default Exp/Contr=0.3,0.1
English Units
Geom File=g01
Flow File=f01
Plan File=p01
Y Axis Title=Elevation
X Axis Title(PF)=Main Channel Distance
X Axis Title(XS)=Station
BEGIN DESCRIPTION:
Finn Creek Trib2T
END DESCRIPTION:
DSS Export Rating Curves= 0
DSS Export Rating Curve Sorted= 0
DSS Export Volume Flow Curves= 0
DXF OffsetX= 0
DXF OffsetY= 0
DXF ScaleX= 1
DXF ScaleY= 10

--- Finn Creek Trib2T.p01 (plan) ---

Plan Title=Multiple Run
Short Identifier=Multiple
Geom File=g01
Flow File=f01
Subcritical Flow
K Sum by GR= 0
Std Step Tol= 0.01
Critical Tol= 0.01
Num of Std Step Trials= 20
Max Error Tol= 0.3
Flow Tol Ratio= 0.001
Split Flow NTrial= 30
Split Flow Tol= 0.02
Split Flow Ratio= 0.02
Log Output Level= 0
Friction Slope Method= 1
Unsteady Friction Slope Method= 2
Unsteady Bridges Friction Slope Method= 1
Parabolic Critical Depth
Global Vel Dist=  1 , 1 , 1
Global Log Level= 0
CheckData=True
Encroach Param= -1, 0, 0, 0
BEGIN DESCRIPTION:
Multiple Run
END DESCRIPTION:

--- Finn Creek Trib2T.f01 (steady flow) ---

Flow Title=Multiple
Number of Profiles=7
Profile Names=10-year,25-year,50-year,1pct_min,100-year,1pct_plu,500-year
River Rch & RM= Finn Creek Trib2,Reach-1,7965
     193     272     337     209     416     831     643
River Rch & RM= Finn Creek Trib2,Reach-1,1741
     248     355     445     279     556    1109     877
Boundary for River Rch & Prof#=Finn Creek Trib2,Reach-1,1
Up Type=0
Dn Type=3
Dn Slope=0.005
Boundary for River Rch & Prof#=Finn Creek Trib2,Reach-1,2
Up Type=0
Dn Type=3
Dn Slope=0.005
Boundary for River Rch & Prof#=Finn Creek Trib2,Reach-1,3
Up Type=0
Dn Type=3
Dn Slope=0.005
Boundary for River Rch & Prof#=Finn Creek Trib2,Reach-1,4
Up Type=0
Dn Type=3
Dn Slope=0.005
Boundary for River Rch & Prof#=Finn Creek Trib2,Reach-1,5
Up Type=0
Dn Type=3
Dn Slope=0.005
Boundary for River Rch & Prof#=Finn Creek Trib2,Reach-1,6
Up Type=0
Dn Type=3
Dn Slope=0.005
Boundary for River Rch & Prof#=Finn Creek Trib2,Reach-1,7
Up Type=0
Dn Type=3
Dn Slope=0.005

--- Finn Creek Trib2T.g01 (geometry) ---

Geom Title=Existing Conditions

River Reach=Finn Creek Trib2,Reach-1
Reach XY= 30
      1353305.00      6830488.00      1353555.00      6830588.00
      1353705.00      6830788.00      1353855.00      6830788.00
      1354205.00      6831088.00      1354405.00      6830988.00
      1354655.00      6830988.00      1354955.00      6831238.00
      1355305.00      6831288.00      1355605.00      6831038.00
      1355755.00      6831138.00      1355955.00      6830988.00
      1356105.00      6830988.00      1356605.00      6831388.00
      1356755.00      6831238.00      1357005.00      6831238.00
      1357105.00      6831138.00      1357205.00      6831138.00
      1357305.00      6831338.00      1357805.00      6831188.00
      1358005.00      6831288.00      1358355.00      6831238.00
      1358405.00      6831388.00      1358534.68      6831457.87
      1358707.46      6831432.54      1358920.45      6831237.99
      1359052.30      6831382.65      1359191.14      6831387.48
      1359598.95      6830895.50      1359855.00      6830938.00

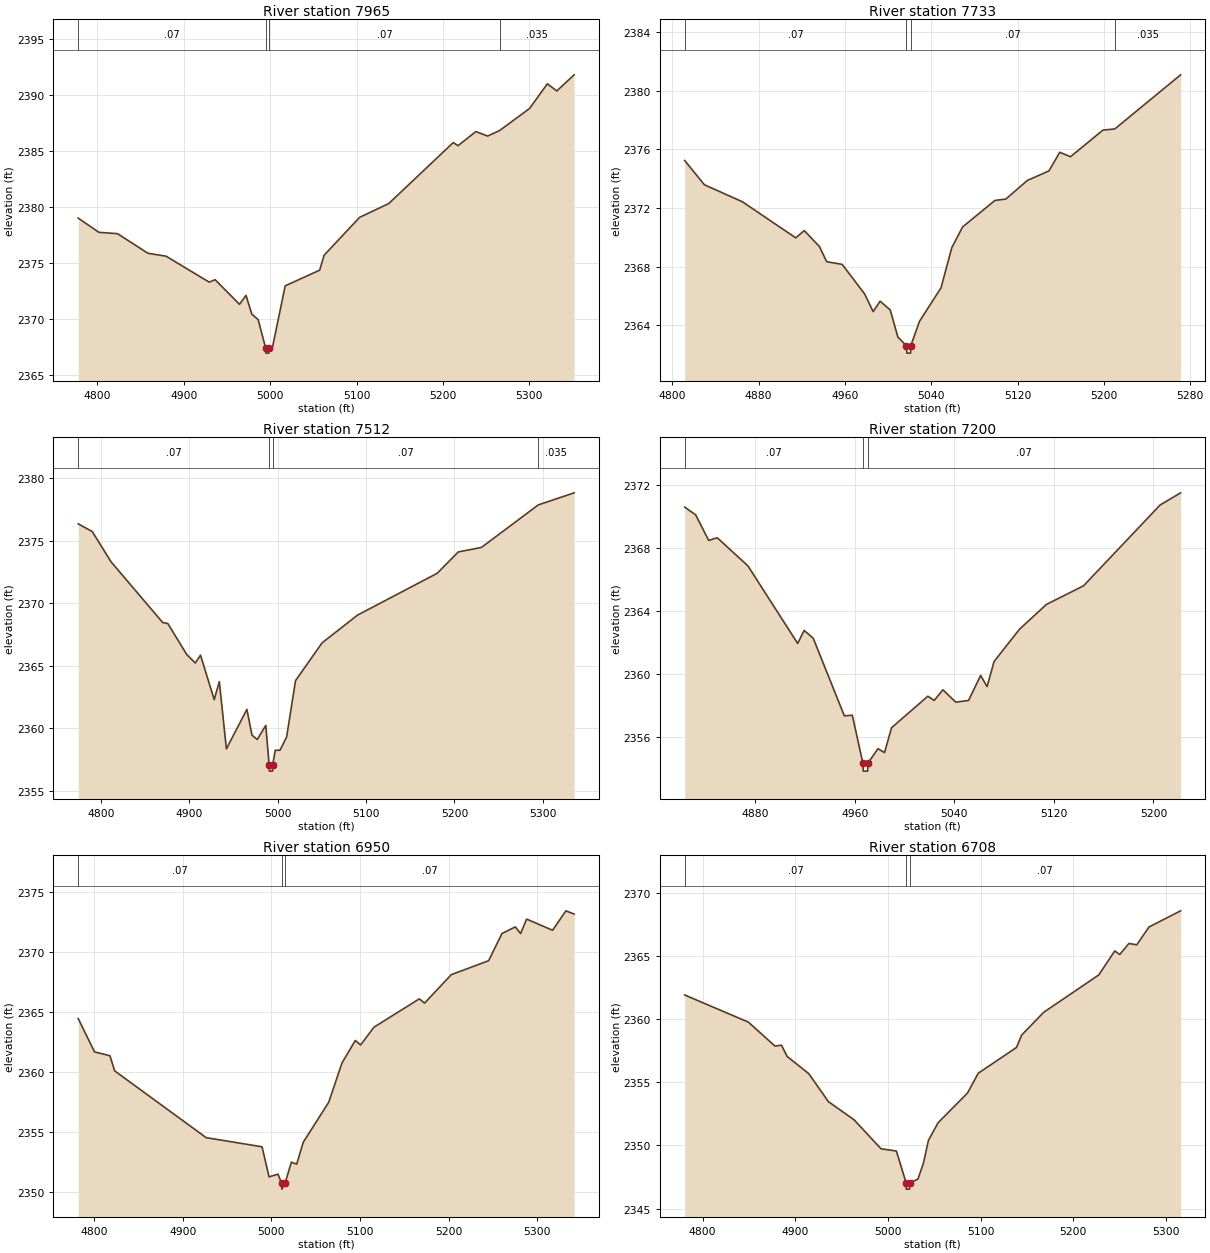
Type RM Length L Ch R = 1,7965,232,232,232
BEGIN DESCRIPTION:
Finn Creek Trib2T 4218
END DESCRIPTION:
XS GIS Cut Line= 3
      1353640.66      6830937.70      1353805.00      6830788.00
      1353713.55      6830448.09
#Sta/Elev= 30
  4777.7 2379.02  4801.7 2377.75  4823.3 2377.63  4858.4 2375.88  4879.4 2375.62
  4929.4 2373.30  4936.2 2373.52  4964.5 2371.32  4972.0 2372.12  4978.7 2370.45
  4986.1 2369.95  4994.6 2367.46  4994.9 2366.96  4998.4 2366.96  4998.6 2367.46
  5002.6 2367.46  5017.4 2372.97  5057.3 2374.37  5062.5 2375.71  5103.6 2379.09
  5137.3 2380.32  5212.0 2385.77  5217.5 2385.49  5238.2 2386.75  5251.9 2386.35
  5265.8 2386.85  5300.3 2388.81  5321.0 2391.02  5331.9 2390.38  5352.0 2391.82
#Mann=4,-1,0
  4777.7    0.07       0  4994.6    0.07       0  4998.6    0.07       0
  5265.8   0.035       0
Bank Sta=4994.6,4998.6
Exp/Cntr=0.3,0.1

Type RM Length L Ch R = 1,7733,221,221,221
BEGIN DESCRIPTION:
Finn Creek Trib2T 4217
END DESCRIPTION:
XS GIS Cut Line= 3
      1353838.53      6831036.70      1353984.14      6830917.14
      1353987.00      6830646.05
#Sta/Elev= 30
  4811.6 2375.23  4829.8 2373.58  4865.0 2372.42  4914.5 2369.96  4922.4 2370.45
  4936.4 2369.37  4943.2 2368.33  4957.5 2368.15  4978.4 2366.13  4986.2 2364.93
  4992.7 2365.64  5002.1 2365.04  5009.1 2363.20  5017.1 2362.60  5017.4 2362.10
  5020.9 2362.10  5021.1 2362.60  5029.1 2364.26  5049.1 2366.55  5059.1 2369.29
  5069.1 2370.70  5099.1 2372.51  5109.1 2372.60  5129.1 2373.87  5149.1 2374.52
  5159.1 2375.79  5169.1 2375.49  5199.1 2377.30  5210.1 2377.38  5271.1 2381.07
#Mann=4,-1,0
  4811.6    0.07       0  5017.1    0.07       0  5021.1    0.07       0
  5210.1   0.035       0
Bank Sta=5017.1,5021.1
Exp/Cntr=0.3,0.1

Type RM Length L Ch R = 1,7512,312,312,312
BEGIN DESCRIPTION:
Finn Creek Trib2T 4216
END DESCRIPTION:
XS GIS Cut Line= 3
      1354039.07      6831232.00      1354155.00      6831038.00
      1354130.22      6830703.32
#Sta/Elev= 30
  4774.0 2376.36  4789.9 2375.74  4811.3 2373.31  4869.7 2368.46  4875.5 2368.38
  4896.9 2365.90  4906.6 2365.22  4912.5 2365.85  4928.0 2362.29  4933.8 2363.73
  4941.8 2358.35  4965.0 2361.51  4970.8 2359.45  4976.7 2359.10  4986.4 2360.23
  4990.2 2357.07  4990.5 2356.57  4994.0 2356.57  4994.2 2357.07  4997.1 2358.24
  5002.5 2358.24  5010.0 2359.30  5020.1 2363.81  5050.1 2366.83  5090.2 2369.05
  5180.5 2372.40  5204.4 2374.11  5230.6 2374.47  5294.9 2377.87  5335.6 2378.84
#Mann=4,-1,0
  4774.0    0.07       0  4990.2    0.07       0  4994.2    0.07       0
  5294.9   0.035       0
Bank Sta=4990.2,4994.2
Exp/Cntr=0.3,0.1

Type RM Length L Ch R = 1,7200,250,250,250
BEGIN DESCRIPTION:
Finn Creek Trib2T 4215
END DESCRIPTION:
XS GIS Cut Line= 3
      1354351.59      6831156.43      1354405.00      6830988.00
      1354354.42      6830772.04
#Sta/Elev= 30
  4823.3 2370.62  4832.1 2370.13  4842.6 2368.50  4849.5 2368.67  4874.1 2366.88
  4914.1 2361.94  4919.3 2362.77  4926.6 2362.27  4951.6 2357.33  4958.0 2357.37
  4966.5 2354.31  4966.8 2353.81  4970.3 2353.81  4970.5 2354.31  4978.6 2355.24
  4983.9 2354.99  4989.5 2356.57  5018.7 2358.58  5023.8 2358.31  5030.8 2358.99
  5041.1 2358.20  5051.4 2358.31  5061.1 2359.90  5066.3 2359.19  5071.9 2360.79
  5092.4 2362.85  5113.9 2364.42  5143.8 2365.61  5205.4 2370.76  5221.8 2371.53
#Mann=3,-1,0
  4823.3    0.07       0  4966.5    0.07       0  4970.5    0.07       0
Bank Sta=4966.5,4970.5
Exp/Cntr=0.3,0.1

Type RM Length L Ch R = 1,6950,242,242,242
BEGIN DESCRIPTION:
Finn Creek Trib2T 4214
END DESCRIPTION:
XS GIS Cut Line= 3
      1354588.56      6831195.52      1354655.00      6830988.00
      1354466.16      6830703.34
#Sta/Elev= 30
  4782.1 2364.49  4800.5 2361.71  4817.9 2361.39  4823.2 2360.13  4926.5 2354.56
  4989.5 2353.80  4997.4 2351.29  5007.5 2351.52  5011.5 2350.77  5011.8 2350.27
  5015.5 2350.77  5022.6 2352.52  5028.6 2352.35  5036.0 2354.18  5064.7 2357.51
  5079.7 2360.79  5094.7 2362.66  5100.7 2362.29  5115.8 2363.77  5166.9 2366.13
  5172.9 2365.78  5203.0 2368.15  5245.1 2369.31  5260.2 2371.58  5275.2 2372.13
  5281.2 2371.58  5288.0 2372.78  5317.3 2371.85  5332.3 2373.47  5341.6 2373.20
#Mann=3,-1,0
  4782.1    0.07       0  5011.5    0.07       0  5015.5    0.07       0
Bank Sta=5011.5,5015.5
Exp/Cntr=0.3,0.1

Type RM Length L Ch R = 1,6708,341,341,341
BEGIN DESCRIPTION:
Finn Creek Trib2T 4213
END DESCRIPTION:
XS GIS Cut Line= 3
      1354624.99      6831263.26      1354805.00      6831138.00
      1354927.11      6830846.55
#Sta/Elev= 30
  4780.7 2361.93  4849.4 2359.78  4878.2 2357.88  4885.2 2357.95  4891.3 2357.06
  4914.7 2355.69  4935.9 2353.47  4963.5 2352.04  4992.6 2349.74  5009.2 2349.56
  5019.7 2347.04  5019.9 2346.54  5023.4 2346.54  5023.7 2347.04  5032.5 2347.34
  5038.4 2348.60  5043.8 2350.40  5054.2 2351.80  5085.9 2354.15  5097.6 2355.73
  5138.9 2357.77  5144.3 2358.74  5168.1 2360.55  5227.7 2363.52  5244.9 2365.42
  5250.3 2365.14  5260.2 2366.01  5268.7 2365.91  5281.9 2367.32  5316.0 2368.60
#Mann=3,-1,0
  4780.7    0.07       0  5019.7    0.07       0  5023.7    0.07       0
Bank Sta=5019.7,5023.7
Exp/Cntr=0.3,0.1

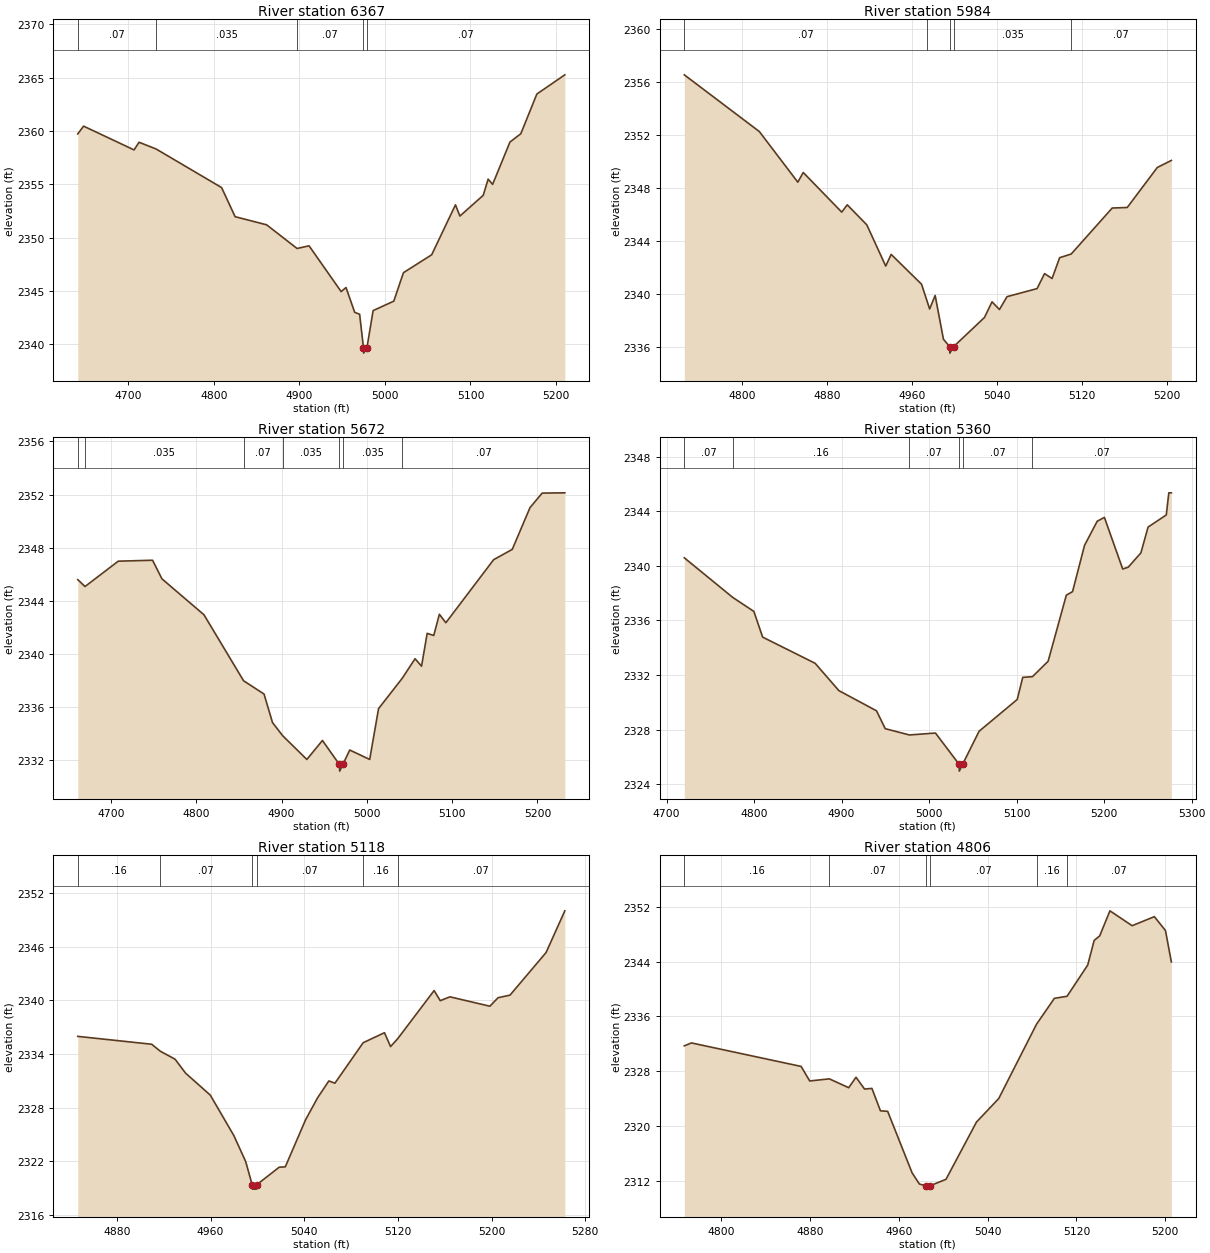
Type RM Length L Ch R = 1,6367,383,383,383
BEGIN DESCRIPTION:
Finn Creek Trib2T 4212
END DESCRIPTION:
XS GIS Cut Line= 3
      1354927.10      6831549.70      1355105.00      6831238.00
      1355044.28      6831036.66
#Sta/Elev= 30
  4641.1 2359.74  4647.9 2360.47  4706.9 2358.24  4712.7 2358.96  4732.6 2358.33
  4809.2 2354.71  4825.0 2351.98  4861.8 2351.22  4897.4 2349.00  4911.4 2349.25
  4948.9 2344.96  4954.6 2345.34  4964.7 2343.02  4970.5 2342.83  4975.0 2339.69
  4975.2 2339.19  4979.0 2339.69  4986.3 2343.18  5010.4 2344.06  5021.7 2346.73
  5054.7 2348.41  5082.5 2353.09  5087.7 2352.04  5114.9 2353.98  5120.7 2355.50
  5125.9 2355.01  5146.2 2358.98  5158.9 2359.76  5177.6 2363.48  5210.3 2365.28
#Mann=5,-1,0
  4641.1    0.07       0  4732.6   0.035       0  4897.4    0.07       0
  4975.0    0.07       0  4979.0    0.07       0
Bank Sta=4975,4979
Exp/Cntr=0.3,0.1

Type RM Length L Ch R = 1,5984,312,312,312
BEGIN DESCRIPTION:
Finn Creek Trib2T 4211
END DESCRIPTION:
XS GIS Cut Line= 3
      1355343.76      6831484.61      1355405.00      6831238.00
      1355260.41      6831093.95
#Sta/Elev= 30
  4745.9 2356.56  4816.5 2352.28  4852.7 2348.46  4857.8 2349.19  4894.0 2346.20
  4899.2 2346.75  4917.6 2345.24  4935.4 2342.13  4940.5 2343.01  4969.1 2340.76
  4974.4 2339.46  4976.7 2338.89  4981.9 2339.91  4989.7 2336.61  4995.4 2336.06
  4995.7 2335.56  4999.4 2336.06  5028.3 2338.25  5035.4 2339.43  5042.4 2338.85
  5049.5 2339.82  5077.8 2340.43  5084.8 2341.56  5091.9 2341.19  5099.0 2342.76
  5109.9 2343.04  5148.5 2346.51  5162.6 2346.55  5190.9 2349.57  5204.1 2350.10
#Mann=5,-1,0
  4745.9    0.07       0  4974.4   0.035       0  4995.4   0.035       0
  4999.4   0.035       0  5109.9    0.07       0
Bank Sta=4995.4,4999.4
Exp/Cntr=0.3,0.1

Type RM Length L Ch R = 1,5672,312,312,312
BEGIN DESCRIPTION:
Finn Creek Trib2T 4210
END DESCRIPTION:
XS GIS Cut Line= 3
      1355570.33      6831375.22      1355605.00      6831038.00
      1355429.82      6830885.74
#Sta/Elev= 30
  4661.0 2345.59  4669.5 2345.07  4708.5 2346.98  4748.7 2347.05  4759.7 2345.65
  4809.0 2342.94  4855.4 2337.97  4879.4 2336.97  4889.4 2334.81  4901.4 2333.82
  4929.6 2332.04  4947.9 2333.47  4967.8 2331.66  4968.1 2331.16  4971.8 2331.66
  4979.9 2332.75  5003.3 2332.04  5013.7 2335.87  5041.4 2338.15  5056.5 2339.63
  5064.1 2339.07  5070.7 2341.54  5078.4 2341.38  5085.0 2342.98  5092.6 2342.34
  5148.6 2347.09  5170.5 2347.87  5191.3 2351.02  5205.6 2352.11  5232.1 2352.13
#Mann=7,-1,0
  4661.0    0.07       0  4669.5   0.035       0  4855.4    0.07       0
  4901.4   0.035       0  4967.8   0.035       0  4971.8   0.035       0
  5041.4    0.07       0
Bank Sta=4967.8,4971.8
Exp/Cntr=0.3,0.1

Type RM Length L Ch R = 1,5360,242,242,242
BEGIN DESCRIPTION:
Finn Creek Trib2T 4209
END DESCRIPTION:
XS GIS Cut Line= 3
      1355841.17      6831367.36      1355855.00      6831088.00
      1355635.42      6830919.47
#Sta/Elev= 30
  4720.3 2340.59  4775.6 2337.69  4799.8 2336.66  4809.8 2334.78  4869.8 2332.86
  4896.9 2330.86  4939.9 2329.38  4949.9 2328.07  4977.5 2327.61  5007.3 2327.75
  5034.3 2325.46  5034.5 2324.96  5038.3 2325.46  5057.1 2327.88  5100.7 2330.21
  5107.0 2331.83  5118.1 2331.88  5136.0 2333.01  5156.8 2337.85  5163.9 2338.11
  5177.6 2341.50  5192.1 2343.27  5200.3 2343.55  5221.2 2339.77  5227.5 2339.90
  5242.0 2340.95  5250.2 2342.84  5271.0 2343.73  5273.9 2345.35  5276.8 2345.35
#Mann=6,-1,0
  4720.3    0.07       0  4775.6    0.16       0  4977.5    0.07       0
  5034.3    0.07       0  5038.3    0.07       0  5118.1    0.07       0
Bank Sta=5034.3,5038.3
Exp/Cntr=0.3,0.1

Type RM Length L Ch R = 1,5118,312,312,312
BEGIN DESCRIPTION:
Finn Creek Trib2T 4208
END DESCRIPTION:
XS GIS Cut Line= 3
      1356041.69      6831140.82      1356055.00      6830988.00
      1355994.92      6830732.47
#Sta/Elev= 30
  4846.6 2335.97  4909.7 2335.09  4917.1 2334.31  4929.7 2333.42  4938.6 2331.87
  4959.8 2329.40  4979.9 2324.88  4990.0 2321.98  4995.5 2319.40  4995.7 2318.90
  4999.2 2318.90  4999.5 2319.40  5018.6 2321.35  5023.8 2321.39  5041.1 2326.64
  5051.4 2329.11  5061.0 2330.99  5066.2 2330.74  5090.3 2335.26  5108.5 2336.38
  5113.7 2334.83  5119.8 2335.71  5150.9 2341.09  5156.1 2339.96  5164.4 2340.39
  5198.5 2339.34  5205.5 2340.29  5215.7 2340.58  5246.5 2345.34  5262.5 2350.00
#Mann=6,-1,0
  4846.6    0.16       0  4917.1    0.07       0  4995.5    0.07       0
  4999.5    0.07       0  5090.3    0.16       0  5119.8    0.07       0
Bank Sta=4995.5,4999.5
Exp/Cntr=0.3,0.1

Type RM Length L Ch R = 1,4806,250,250,250
BEGIN DESCRIPTION:
Finn Creek Trib2T 4207
END DESCRIPTION:
XS GIS Cut Line= 3
      1356127.64      6831289.26      1356305.00      6831138.00
      1356312.51      6830932.74
#Sta/Elev= 30
  4766.9 2331.70  4773.3 2332.13  4872.1 2328.70  4879.8 2326.58  4897.5 2326.89
  4914.9 2325.60  4921.5 2327.12  4929.2 2325.40  4935.8 2325.50  4943.5 2322.23
  4950.0 2322.15  4972.0 2313.18  4978.6 2311.55  4984.3 2311.31  4984.5 2310.81
  4988.3 2311.31  5002.5 2312.24  5030.0 2320.60  5050.0 2324.02  5084.0 2334.85
  5100.1 2338.63  5111.5 2338.93  5130.1 2343.48  5135.9 2347.07  5140.9 2347.74
  5150.1 2351.39  5170.1 2349.22  5190.1 2350.54  5200.1 2348.52  5205.4 2343.94
#Mann=6,-1,0
  4766.9    0.16       0  4897.5    0.07       0  4984.3    0.07       0
  4988.3    0.07       0  5084.0    0.16       0  5111.5    0.07       0
Bank Sta=4984.3,4988.3
Exp/Cntr=0.3,0.1

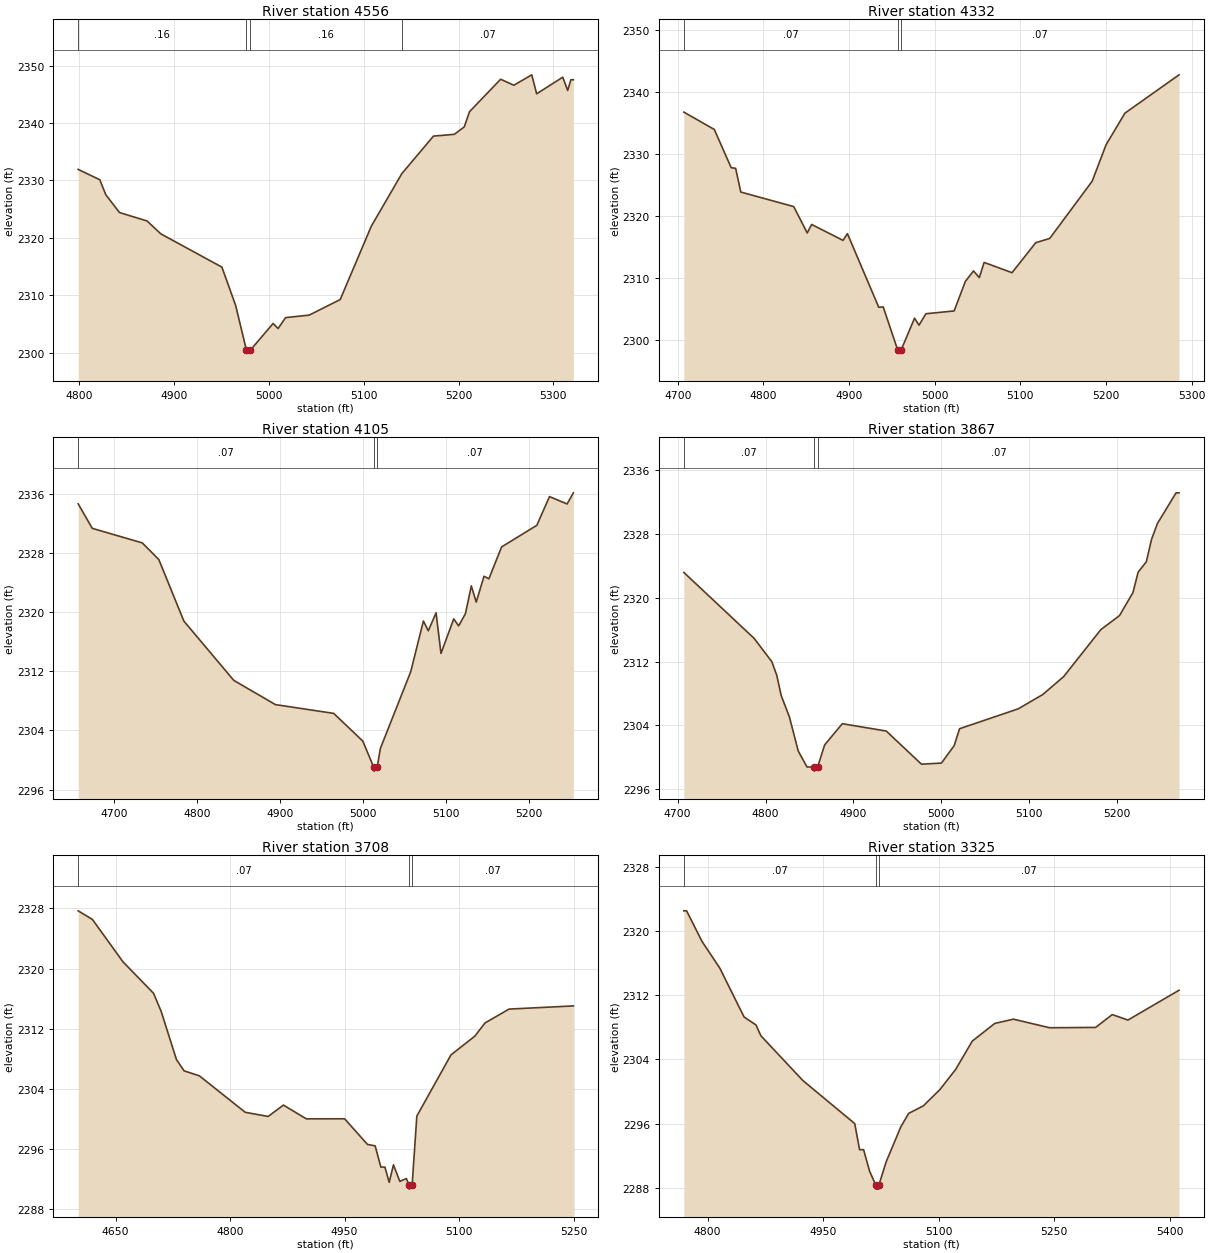
Type RM Length L Ch R = 1,4556,224,224,224
BEGIN DESCRIPTION:
Finn Creek Trib2T 4206
END DESCRIPTION:
XS GIS Cut Line= 3
      1356322.94      6831437.71      1356482.05      6831315.05
      1356388.04      6831008.03
#Sta/Elev= 30
  4799.1 2331.93  4821.9 2330.13  4828.2 2327.53  4842.7 2324.42  4871.7 2322.96
  4886.2 2320.72  4950.6 2314.93  4965.1 2308.26  4976.5 2300.47  4976.7 2299.97
  4980.5 2300.47  5004.6 2305.13  5009.8 2304.25  5017.8 2306.15  5042.6 2306.58
  5075.3 2309.29  5108.1 2322.05  5140.3 2331.20  5173.6 2337.72  5195.6 2338.03
  5206.1 2339.33  5211.6 2341.96  5244.4 2347.61  5258.4 2346.57  5277.2 2348.38
  5282.4 2345.08  5309.9 2347.97  5315.1 2345.66  5318.5 2347.53  5321.1 2347.53
#Mann=4,-1,0
  4799.1    0.16       0  4976.5    0.07       0  4980.5    0.16       0
  5140.3    0.07       0
Bank Sta=4976.5,4980.5
Exp/Cntr=0.3,0.1

Type RM Length L Ch R = 1,4332,227,227,227
BEGIN DESCRIPTION:
Finn Creek Trib2T 4205
END DESCRIPTION:
XS GIS Cut Line= 3
      1356585.95      6831622.64      1356655.00      6831338.00
      1356520.87      6831086.19
#Sta/Elev= 30
  4707.1 2336.75  4742.7 2333.95  4762.4 2327.80  4767.6 2327.70  4773.6 2323.88
  4835.4 2321.54  4851.2 2317.29  4856.3 2318.66  4893.0 2316.10  4898.1 2317.18
  4934.7 2305.33  4939.9 2305.39  4956.8 2298.45  4957.1 2297.95  4960.8 2298.45
  4976.5 2303.58  4981.7 2302.45  4989.7 2304.29  5022.7 2304.74  5035.8 2309.49
  5045.3 2311.18  5052.1 2310.11  5057.7 2312.55  5090.3 2310.90  5118.0 2315.73
  5134.3 2316.41  5183.9 2325.63  5200.2 2331.52  5222.1 2336.58  5285.3 2342.75
#Mann=3,-1,0
  4707.1    0.07       0  4956.8    0.07       0  4960.8    0.07       0
Bank Sta=4956.8,4960.8
Exp/Cntr=0.3,0.1

Type RM Length L Ch R = 1,4105,238,238,238
BEGIN DESCRIPTION:
Finn Creek Trib2T 4204
END DESCRIPTION:
XS GIS Cut Line= 3
      1356799.49      6831554.95      1356829.99      6831213.01
      1356695.34      6830997.63
#Sta/Elev= 30
  4656.7 2334.69  4673.7 2331.37  4734.0 2329.40  4754.0 2327.14  4784.2 2318.81
  4844.4 2310.78  4894.6 2307.50  4964.9 2306.31  5000.0 2302.56  5013.3 2298.99
  5013.6 2298.49  5017.3 2298.99  5021.2 2301.56  5057.8 2311.95  5073.1 2318.82
  5079.0 2317.50  5088.4 2319.93  5094.3 2314.43  5109.7 2319.11  5115.6 2318.16
  5123.8 2319.81  5130.9 2323.58  5136.8 2321.38  5146.2 2324.88  5152.1 2324.54
  5167.4 2328.85  5209.9 2331.78  5225.2 2335.67  5246.4 2334.67  5254.0 2336.18
#Mann=3,-1,0
  4656.7    0.07       0  5013.3    0.07       0  5017.3    0.07       0
Bank Sta=5013.3,5017.3
Exp/Cntr=0.3,0.1

Type RM Length L Ch R = 1,3867,159,159,159
BEGIN DESCRIPTION:
Finn Creek Trib2T 4203
END DESCRIPTION:
XS GIS Cut Line= 3
      1357015.64      6831508.00      1357027.65      6831215.35
      1356882.85      6830987.23
#Sta/Elev= 30
  4707.1 2323.16  4787.2 2314.88  4807.2 2311.97  4812.8 2310.26  4817.8 2307.74
  4827.2 2305.04  4837.2 2300.78  4847.2 2298.79  4855.2 2298.77  4855.5 2298.27
  4859.2 2298.77  4867.2 2301.55  4887.3 2304.21  4937.3 2303.29  4977.3 2299.14
  5000.0 2299.28  5014.5 2301.46  5020.6 2303.58  5087.3 2306.07  5115.3 2307.87
  5139.0 2310.11  5181.3 2316.00  5202.5 2317.75  5217.8 2320.64  5223.7 2323.20
  5233.0 2324.49  5238.9 2327.29  5245.6 2329.28  5266.8 2333.13  5270.2 2333.13
#Mann=3,-1,0
  4707.1    0.07       0  4855.2    0.07       0  4859.2    0.07       0
Bank Sta=4855.2,4859.2
Exp/Cntr=0.3,0.1

Type RM Length L Ch R = 1,3708,383,383,383
BEGIN DESCRIPTION:
Finn Creek Trib2T 4201
END DESCRIPTION:
XS GIS Cut Line= 3
      1357169.29      6831536.64      1357155.00      6831138.00
      1357044.29      6830914.29
#Sta/Elev= 30
  4601.1 2327.68  4619.8 2326.53  4659.8 2320.90  4699.8 2316.72  4709.8 2314.31
  4729.8 2307.91  4739.8 2306.41  4759.8 2305.75  4819.9 2300.90  4849.9 2300.35
  4869.9 2301.86  4899.9 2300.03  4950.0 2300.04  4980.0 2296.63  4990.0 2296.44
  4997.5 2293.62  5002.8 2293.62  5008.4 2291.59  5014.0 2293.92  5022.3 2291.72
  5030.9 2292.10  5034.4 2291.19  5034.7 2290.69  5038.4 2291.19  5044.6 2300.40
  5089.3 2308.53  5120.6 2311.03  5133.9 2312.78  5165.4 2314.62  5249.6 2315.04
#Mann=3,-1,0
  4601.1    0.07       0  5034.4    0.07       0  5038.4    0.07       0
Bank Sta=5034.4,5038.4
Exp/Cntr=0.3,0.1

Type RM Length L Ch R = 1,3325,171,171,171
BEGIN DESCRIPTION:
Finn Creek Trib2T 4202
END DESCRIPTION:
XS GIS Cut Line= 3
      1357263.04      6831549.69      1357355.00      6831338.00
      1357281.31      6830932.75
#Sta/Elev= 30
  4769.2 2322.55  4772.8 2322.55  4792.8 2318.73  4815.9 2315.40  4847.4 2309.30
  4862.8 2308.31  4869.2 2306.96  4923.7 2301.37  4991.0 2296.00  4997.3 2292.74
  5002.5 2292.74  5010.2 2290.08  5018.3 2288.32  5018.6 2287.82  5022.1 2287.82
  5022.3 2288.32  5031.8 2291.23  5050.8 2295.59  5061.0 2297.27  5080.0 2298.21
  5101.6 2300.25  5122.0 2302.76  5143.6 2306.30  5172.8 2308.50  5196.9 2309.03
  5243.9 2307.96  5303.6 2308.00  5325.2 2309.60  5345.6 2308.92  5411.9 2312.64
#Mann=3,-1,0
  4769.2    0.07       0  5018.3    0.07       0  5022.3    0.07       0
Bank Sta=5018.3,5022.3
Exp/Cntr=0.3,0.1

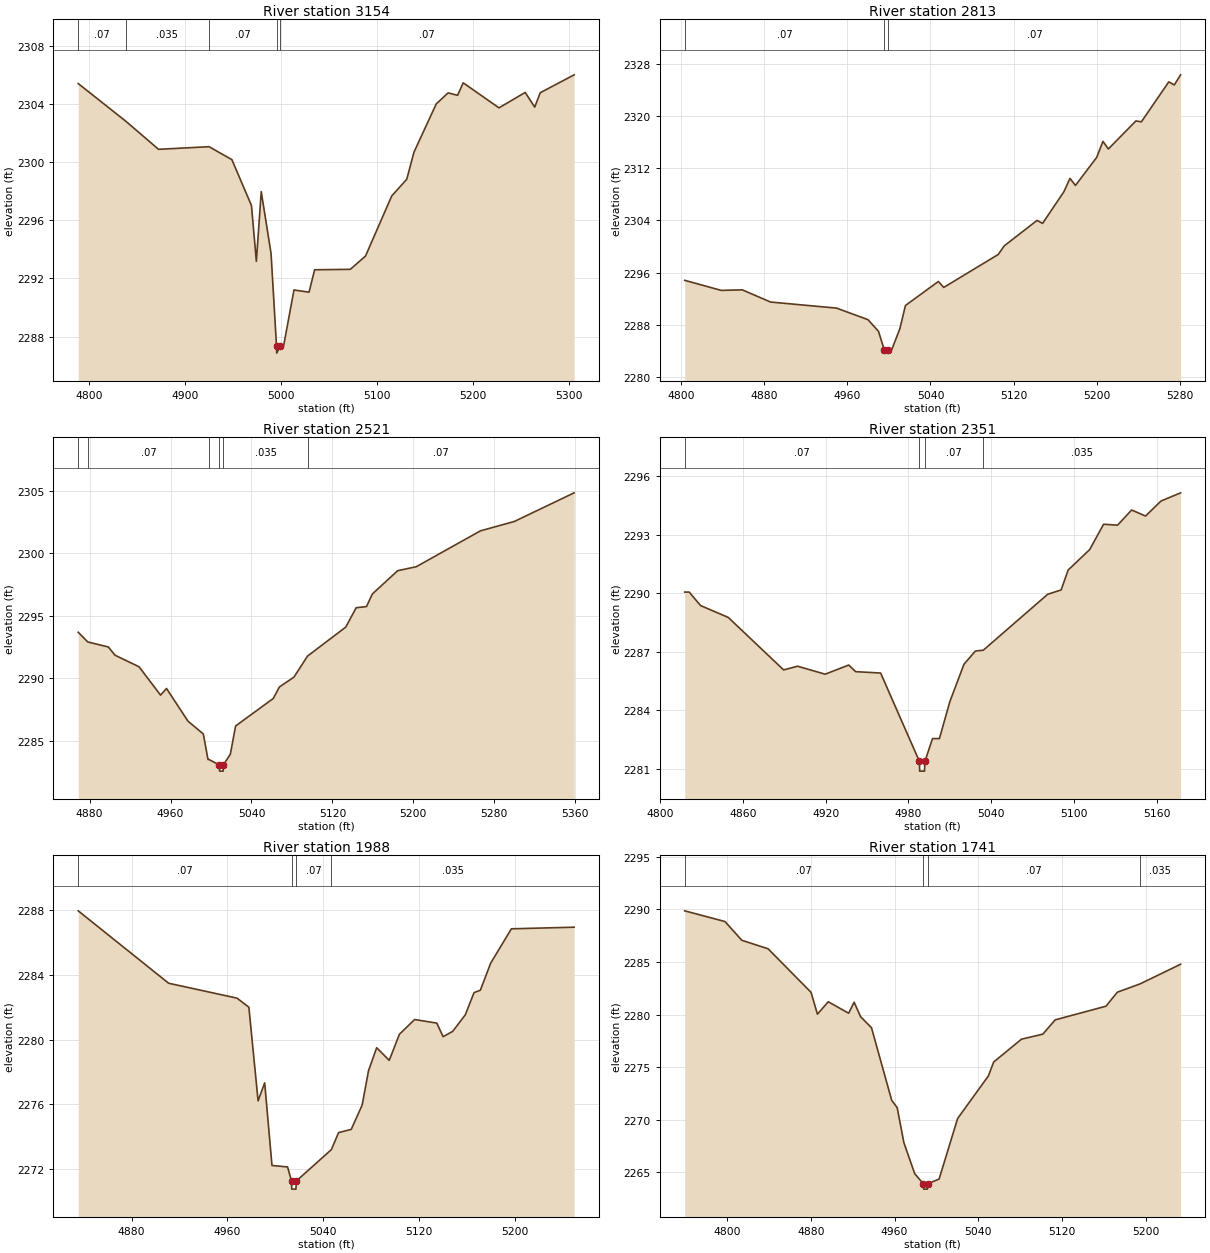
Type RM Length L Ch R = 1,3154,341,341,341
BEGIN DESCRIPTION:
Finn Creek Trib2T 4200
END DESCRIPTION:
XS GIS Cut Line= 3
      1357463.56      6831494.99      1357505.00      6831288.00
      1357351.60      6831023.69
#Sta/Elev= 30
  4788.9 2305.40  4838.5 2302.81  4872.6 2300.88  4925.2 2301.06  4949.0 2300.17
  4969.4 2297.02  4974.5 2293.18  4979.6 2297.97  4989.8 2293.73  4995.5 2287.37
  4995.7 2286.87  4999.5 2287.37  5002.9 2287.37  5013.7 2291.21  5029.4 2291.06
  5035.2 2292.60  5072.4 2292.63  5088.2 2293.54  5115.6 2297.68  5131.2 2298.82
  5138.7 2300.68  5161.9 2304.00  5174.3 2304.76  5184.2 2304.59  5190.0 2305.45
  5227.3 2303.73  5254.6 2304.79  5264.5 2303.78  5270.3 2304.77  5305.6 2306.00
#Mann=5,-1,0
  4788.9    0.07       0  4838.5   0.035       0  4925.2    0.07       0
  4995.5    0.07       0  4999.5    0.07       0
Bank Sta=4995.5,4999.5
Exp/Cntr=0.3,0.1

Type RM Length L Ch R = 1,2813,292,292,292
BEGIN DESCRIPTION:
Finn Creek Trib2T 4199
END DESCRIPTION:
XS GIS Cut Line= 3
      1357778.66      6831383.03      1357805.00      6831188.00
      1357716.74      6830921.22
#Sta/Elev= 30
  4803.2 2294.83  4838.5 2293.28  4858.7 2293.37  4885.9 2291.50  4949.5 2290.57
  4979.8 2288.80  4989.9 2287.02  4995.5 2284.17  4995.7 2283.67  4999.5 2284.17
  5002.6 2284.17  5010.5 2287.40  5015.9 2290.97  5047.6 2294.65  5052.8 2293.74
  5105.3 2298.79  5111.0 2300.10  5142.7 2304.01  5148.0 2303.55  5168.5 2308.39
  5174.4 2310.45  5179.7 2309.37  5200.1 2313.66  5206.2 2316.12  5211.4 2314.96
  5237.9 2319.25  5243.2 2319.12  5269.6 2325.24  5274.9 2324.77  5281.0 2326.32
#Mann=3,-1,0
  4803.2    0.07       0  4995.5    0.07       0  4999.5    0.07       0
Bank Sta=4995.5,4999.5
Exp/Cntr=0.3,0.1

Type RM Length L Ch R = 1,2521,170,170,170
BEGIN DESCRIPTION:
Finn Creek Trib2T 4198
END DESCRIPTION:
XS GIS Cut Line= 3
      1357984.37      6831398.69      1358055.00      6831288.00
      1357976.57      6830937.67
#Sta/Elev= 30
  4868.7 2293.70  4878.2 2292.92  4898.5 2292.52  4905.1 2291.86  4928.8 2290.94
  4950.1 2288.67  4956.0 2289.20  4977.2 2286.59  4992.4 2285.56  4997.0 2283.52
  4997.9 2283.52  5008.2 2283.09  5008.5 2282.59  5012.0 2282.59  5012.2 2283.09
  5019.1 2283.94  5024.3 2286.20  5061.5 2288.40  5067.6 2289.32  5082.0 2290.11
  5095.4 2291.79  5133.2 2294.11  5143.5 2295.66  5153.7 2295.75  5159.5 2296.76
  5184.5 2298.62  5202.9 2298.94  5266.4 2301.81  5299.9 2302.56  5359.0 2304.85
#Mann=6,-1,0
  4868.7   0.035       0  4878.2    0.07       0  4997.9   0.035       0
  5008.2   0.035       0  5012.2   0.035       0  5095.4    0.07       0
Bank Sta=5008.2,5012.2
Exp/Cntr=0.3,0.1

Type RM Length L Ch R = 1,2351,363,363,363
BEGIN DESCRIPTION:
Finn Creek Trib2T 4197
END DESCRIPTION:
XS GIS Cut Line= 3
      1358190.12      6831419.49      1358205.00      6831238.00
      1358177.13      6831062.90
#Sta/Elev= 30
  4817.9 2290.05  4821.2 2290.05  4829.4 2289.36  4849.5 2288.75  4889.6 2286.06
  4899.7 2286.25  4919.7 2285.84  4936.8 2286.31  4941.8 2285.97  4959.9 2285.90
  4988.0 2281.37  4988.2 2280.87  4991.7 2280.87  4992.0 2281.37  4997.5 2282.54
  5002.5 2282.54  5010.1 2284.44  5020.3 2286.35  5028.6 2287.03  5034.3 2287.07
  5081.0 2289.94  5090.7 2290.16  5095.8 2291.18  5111.4 2292.23  5121.5 2293.53
  5131.6 2293.48  5141.8 2294.26  5151.9 2293.95  5163.1 2294.72  5177.3 2295.14
#Mann=4,-1,0
  4817.9    0.07       0  4988.0    0.07       0  4992.0    0.07       0
  5034.3   0.035       0
Bank Sta=4988,4992
Exp/Cntr=0.3,0.1

Type RM Length L Ch R = 1,1988,247,247,247
BEGIN DESCRIPTION:
Finn Creek Trib2T 4196
END DESCRIPTION:
XS GIS Cut Line= 3
      1358255.19      6831455.96      1358405.00      6831388.00
      1358486.69      6831152.15
#Sta/Elev= 30
  4835.5 2287.95  4911.0 2283.48  4968.1 2282.56  4978.0 2282.00  4985.7 2276.22
  4991.2 2277.33  4997.3 2272.23  5010.3 2272.14  5013.6 2271.27  5013.8 2270.77
  5017.3 2270.77  5017.6 2271.27  5046.9 2273.21  5052.9 2274.26  5063.5 2274.46
  5072.6 2275.96  5077.9 2278.08  5084.7 2279.50  5095.2 2278.72  5103.7 2280.33
  5116.4 2281.24  5134.9 2281.02  5140.2 2280.18  5148.2 2280.51  5158.7 2281.53
  5166.0 2282.90  5171.3 2283.05  5179.9 2284.72  5197.2 2286.84  5249.6 2286.94
#Mann=4,-1,0
  4835.5    0.07       0  5013.6    0.07       0  5017.6    0.07       0
  5046.9   0.035       0
Bank Sta=5013.6,5017.6
Exp/Cntr=0.3,0.1

Type RM Length L Ch R = 1,1741,249,249,249
BEGIN DESCRIPTION:
Finn Creek Trib2T 4195
END DESCRIPTION:
XS GIS Cut Line= 3
      1358560.71      6831670.85      1358619.49      6831437.85
      1358578.14      6831208.55
#Sta/Elev= 30
  4759.7 2289.87  4798.2 2288.85  4814.2 2287.07  4839.3 2286.26  4880.3 2282.12
  4886.4 2280.04  4896.7 2281.22  4916.2 2280.13  4921.4 2281.18  4927.6 2279.80
  4938.0 2278.75  4957.3 2271.84  4962.5 2271.15  4968.9 2267.82  4979.2 2264.88
  4987.5 2263.90  4987.8 2263.40  4991.3 2263.40  4991.5 2263.90  5002.5 2264.36
  5020.2 2270.12  5049.5 2274.16  5054.6 2275.49  5081.1 2277.66  5101.5 2278.14
  5113.3 2279.50  5161.8 2280.80  5172.6 2282.13  5194.3 2282.92  5233.0 2284.79
#Mann=4,-1,0
  4759.7    0.07       0  4987.5    0.07       0  4991.5    0.07       0
  5194.3   0.035       0
Bank Sta=4987.5,4991.5
Exp/Cntr=0.3,0.1

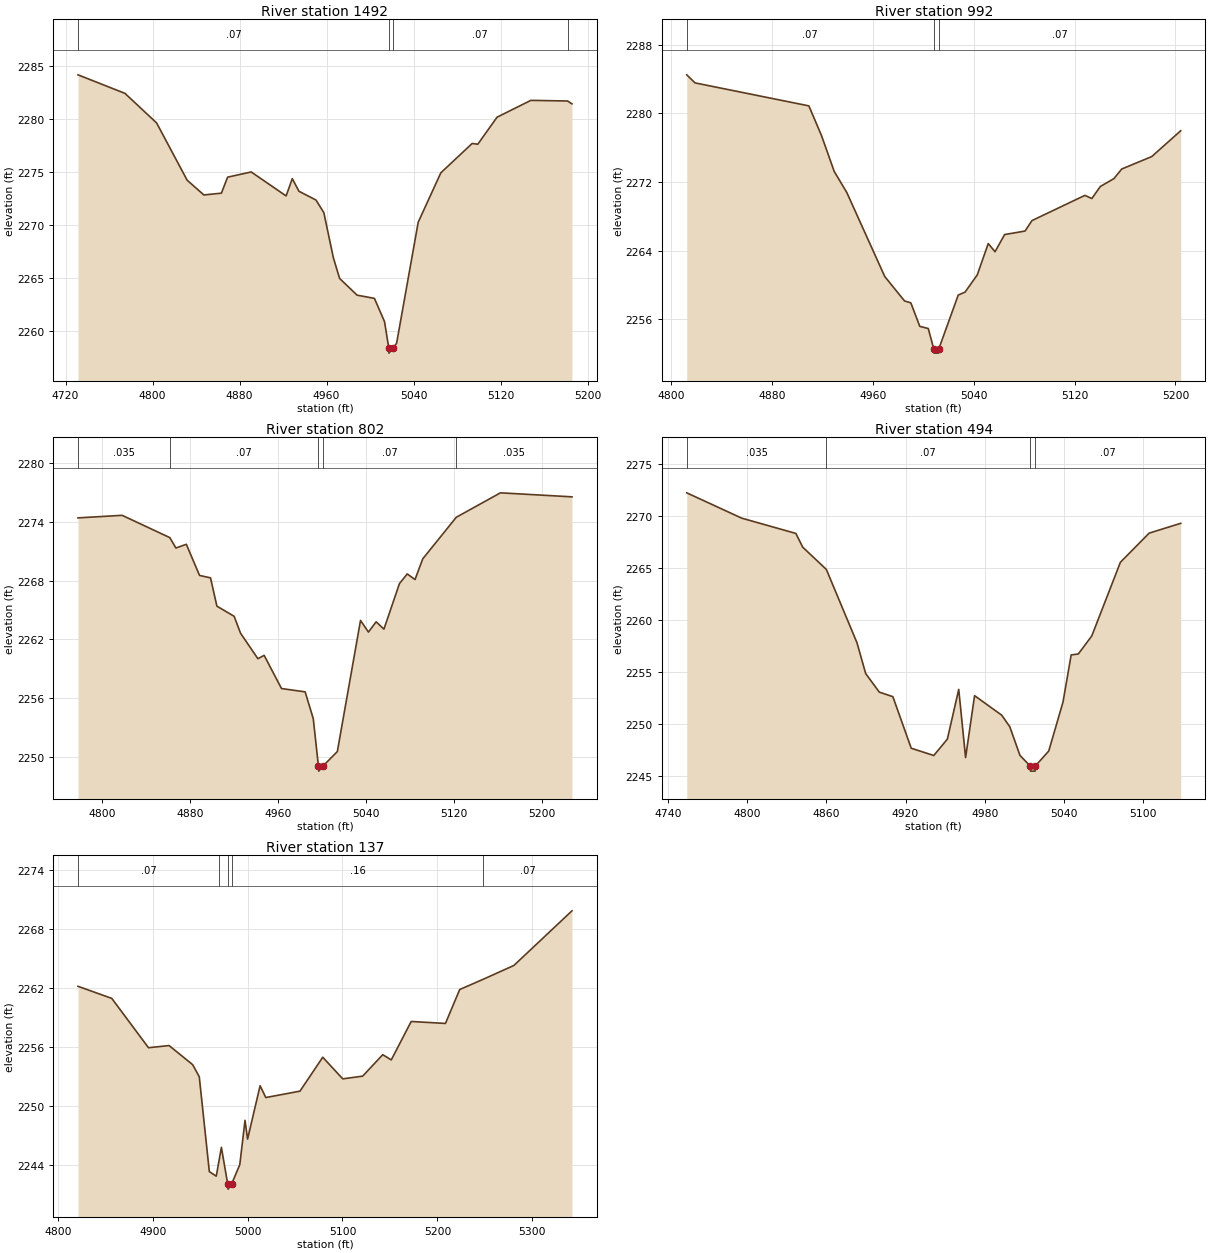
Type RM Length L Ch R = 1,1492,500,500,500
BEGIN DESCRIPTION:
Finn Creek Trib2T 1770
END DESCRIPTION:
XS GIS Cut Line= 3
      1358935.26      6831545.82      1358805.18      6831310.82
      1358756.87      6831131.51
#Sta/Elev= 30
  4731.4 2284.18  4774.6 2282.43  4803.7 2279.64  4831.8 2274.23  4847.2 2272.84
  4863.3 2273.01  4869.0 2274.52  4890.7 2275.01  4922.8 2272.75  4928.5 2274.38
  4934.6 2273.19  4950.3 2272.36  4957.5 2271.17  4966.3 2266.90  4972.0 2264.96
  4988.1 2263.38  5004.0 2263.08  5013.3 2260.89  5017.2 2258.41  5017.4 2257.91
  5021.2 2258.41  5024.4 2258.83  5044.3 2270.27  5065.1 2274.93  5093.9 2277.70
  5099.1 2277.63  5116.8 2280.18  5147.9 2281.77  5181.6 2281.71  5185.7 2281.44
#Mann=4,-1,0
  4731.4    0.07       0  5017.2    0.07       0  5021.2    0.07       0
  5181.6   0.035       0
Bank Sta=5017.2,5021.2
Exp/Cntr=0.3,0.1

Type RM Length L Ch R = 1,992,190,190,190
BEGIN DESCRIPTION:
Finn Creek Trib2 1.0
END DESCRIPTION:
XS GIS Cut Line= 3
      1359176.21      6831574.59      1359191.14      6831387.48
      1359112.23      6831199.14
#Sta/Elev= 30
  4812.3 2284.48  4818.9 2283.54  4909.2 2280.86  4919.2 2277.41  4929.3 2273.22
  4939.3 2270.76  4969.4 2260.97  4985.1 2258.12  4990.1 2257.90  4997.2 2255.16
  5003.9 2254.91  5008.3 2252.54  5008.5 2252.04  5012.0 2252.04  5012.3 2252.54
  5027.7 2258.81  5033.1 2259.15  5042.8 2261.16  5051.5 2264.81  5056.9 2263.86
  5064.5 2265.86  5080.7 2266.27  5086.2 2267.49  5128.2 2270.43  5133.7 2270.06
  5140.4 2271.46  5151.2 2272.38  5157.4 2273.50  5181.2 2274.95  5204.2 2277.96
#Mann=3,-1,0
  4812.3    0.07       0  5008.3    0.07       0  5012.3    0.07       0
Bank Sta=5008.3,5012.3
Exp/Cntr=0.3,0.1

Type RM Length L Ch R = 1,802,308,308,308
BEGIN DESCRIPTION:
Finn Creek Trib2T 4194
END DESCRIPTION:
XS GIS Cut Line= 3
      1359442.72      6831453.33      1359331.67      6831261.34
      1359171.86      6831099.14
#Sta/Elev= 30
  4778.2 2274.40  4818.4 2274.66  4861.8 2272.38  4867.3 2271.32  4876.8 2271.70
  4888.8 2268.52  4898.8 2268.27  4904.6 2265.38  4920.3 2264.34  4926.1 2262.62
  4941.9 2260.01  4947.6 2260.35  4963.4 2256.96  4984.9 2256.62  4992.3 2253.88
  4997.0 2249.02  4997.3 2248.52  5001.0 2249.02  5014.2 2250.52  5035.3 2263.92
  5042.5 2262.73  5049.5 2263.78  5056.6 2263.03  5070.7 2267.68  5077.8 2268.67
  5084.9 2268.10  5091.9 2270.21  5122.4 2274.46  5162.6 2276.96  5227.7 2276.55
#Mann=5,-1,0
  4778.2   0.035       0  4861.8    0.07       0  4997.0    0.07       0
  5001.0    0.07       0  5122.4   0.035       0
Bank Sta=4997,5001
Exp/Cntr=0.3,0.1

Type RM Length L Ch R = 1,494,357,357,357
BEGIN DESCRIPTION:
Bitter Creek Trib14T3 4.0
END DESCRIPTION:
XS GIS Cut Line= 3
      1359541.08      6831249.52      1359481.18      6831011.13
      1359363.02      6830960.63
#Sta/Elev= 30
  4754.2 2272.22  4795.8 2269.79  4836.9 2268.32  4842.1 2267.00  4860.0 2264.86
  4883.2 2257.82  4889.8 2254.86  4900.1 2253.08  4910.4 2252.64  4924.3 2247.69
  4941.4 2246.99  4951.7 2248.57  4960.3 2253.34  4965.5 2246.79  4972.3 2252.74
  4992.9 2250.86  4999.0 2249.75  5006.7 2247.00  5014.4 2245.99  5014.7 2245.49
  5018.2 2245.49  5018.4 2245.99  5028.5 2247.42  5039.3 2252.12  5045.5 2256.65
  5050.9 2256.74  5061.1 2258.47  5082.8 2265.55  5104.6 2268.35  5128.5 2269.29
#Mann=4,-1,0
  4754.2   0.035       0  4860.0    0.07       0  5014.4    0.07       0
  5018.4    0.07       0
Bank Sta=5014.4,5018.4
Exp/Cntr=0.3,0.1

Type RM Length L Ch R = 1,137,0,0,0
BEGIN DESCRIPTION:
Finn Creek Trib2T 4193
END DESCRIPTION:
XS GIS Cut Line= 3
      1359697.92      6831057.55      1359760.93      6830890.33
      1359476.55      6830700.72
#Sta/Elev= 30
  4821.3 2262.16  4856.9 2260.93  4895.6 2255.91  4917.3 2256.13  4942.2 2254.18
  4949.1 2252.95  4959.7 2243.30  4967.0 2242.84  4969.9 2244.41  4972.4 2245.77
  4979.1 2242.02  4979.4 2241.52  4983.1 2242.02  4991.8 2244.02  4997.3 2248.52
  5000.0 2246.61  5013.2 2252.04  5019.2 2250.84  5055.2 2251.49  5079.2 2254.94
  5100.3 2252.74  5121.3 2253.02  5142.4 2255.20  5151.4 2254.67  5172.4 2258.58
  5208.5 2258.38  5223.5 2261.83  5248.4 2262.88  5280.6 2264.28  5341.8 2269.84
#Mann=5,-1,0
  4821.3    0.07       0  4969.9    0.16       0  4979.1    0.07       0
  4983.1    0.16       0  5248.4    0.07       0
Bank Sta=4979.1,4983.1
Exp/Cntr=0.3,0.1

Chan Stop Cuts=-1