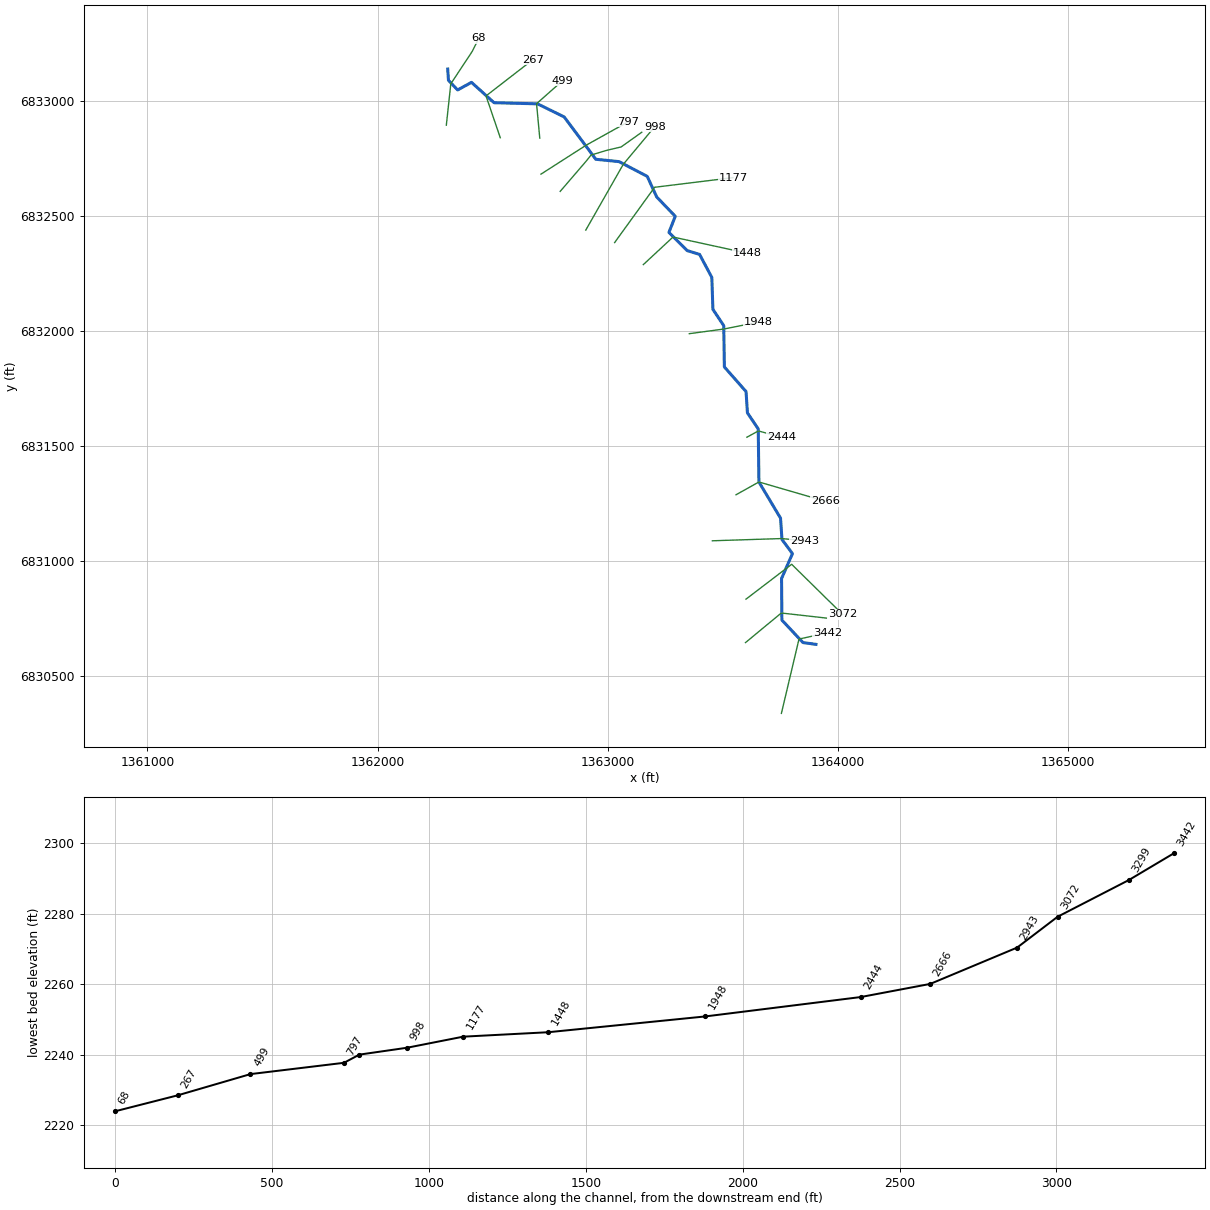
--- Finn Creek Trib3.prj (project) ---

Proj Title=Finn Creek Trib3 Base Level Engineering
Current Plan=p01
Default Exp/Contr=0.3,0.1
English Units
Geom File=g01
Flow File=f01
Plan File=p01
Y Axis Title=Elevation
X Axis Title(PF)=Main Channel Distance
X Axis Title(XS)=Station
BEGIN DESCRIPTION:
Finn Creek Trib3
END DESCRIPTION:
DSS Export Rating Curves= 0
DSS Export Rating Curve Sorted= 0
DSS Export Volume Flow Curves= 0
DXF OffsetX= 0
DXF OffsetY= 0
DXF ScaleX= 1
DXF ScaleY= 10

--- Finn Creek Trib3.p01 (plan) ---

Plan Title=Multiple Run
Short Identifier=Multiple
Geom File=g01
Flow File=f01
Subcritical Flow
K Sum by GR= 0
Std Step Tol= 0.01
Critical Tol= 0.01
Num of Std Step Trials= 20
Max Error Tol= 0.3
Flow Tol Ratio= 0.001
Split Flow NTrial= 30
Split Flow Tol= 0.02
Split Flow Ratio= 0.02
Log Output Level= 0
Friction Slope Method= 1
Unsteady Friction Slope Method= 2
Unsteady Bridges Friction Slope Method= 1
Parabolic Critical Depth
Global Vel Dist=  1 , 1 , 1
Global Log Level= 0
CheckData=True
Encroach Param= -1, 0, 0, 0
BEGIN DESCRIPTION:
Multiple Run
END DESCRIPTION:

--- Finn Creek Trib3.f01 (steady flow) ---

Flow Title=Multiple
Number of Profiles=7
Profile Names=10-year,25-year,50-year,1pct_min,100-year,1pct_plu,500-year
River Rch & RM= Finn Creek Trib3,Reach-1,3442
      99     133     161      97     194     387     284
Boundary for River Rch & Prof#=Finn Creek Trib3,Reach-1,1
Up Type=0
Dn Type=3
Dn Slope=0.005
Boundary for River Rch & Prof#=Finn Creek Trib3,Reach-1,2
Up Type=0
Dn Type=3
Dn Slope=0.005
Boundary for River Rch & Prof#=Finn Creek Trib3,Reach-1,3
Up Type=0
Dn Type=3
Dn Slope=0.005
Boundary for River Rch & Prof#=Finn Creek Trib3,Reach-1,4
Up Type=0
Dn Type=3
Dn Slope=0.005
Boundary for River Rch & Prof#=Finn Creek Trib3,Reach-1,5
Up Type=0
Dn Type=3
Dn Slope=0.005
Boundary for River Rch & Prof#=Finn Creek Trib3,Reach-1,6
Up Type=0
Dn Type=3
Dn Slope=0.005
Boundary for River Rch & Prof#=Finn Creek Trib3,Reach-1,7
Up Type=0
Dn Type=3
Dn Slope=0.005

--- Finn Creek Trib3.g01 (geometry) ---

Geom Title=Existing Conditions

River Reach=Finn Creek Trib3,Reach-1
Reach XY= 30
      1363905.00      6830638.00      1363848.76      6830645.75
      1363757.16      6830743.43      1363755.70      6830924.09
      1363803.06      6831032.29      1363757.50      6831093.56
      1363751.17      6831186.42      1363657.35      6831343.52
      1363654.32      6831574.08      1363607.36      6831643.98
      1363601.38      6831736.50      1363507.18      6831843.45
      1363504.48      6832022.78      1363457.39      6832093.53
      1363452.65      6832232.50      1363399.41      6832332.39
      1363345.54      6832348.89      1363266.24      6832427.98
      1363293.74      6832497.99      1363213.20      6832581.97
      1363172.05      6832671.51      1363049.44      6832735.55
      1362948.55      6832745.74      1362811.07      6832929.87
      1362695.35      6832986.64      1362506.46      6832991.56
      1362408.32      6833080.00      1362348.11      6833046.98
      1362308.27      6833088.64      1362305.00      6833138.00

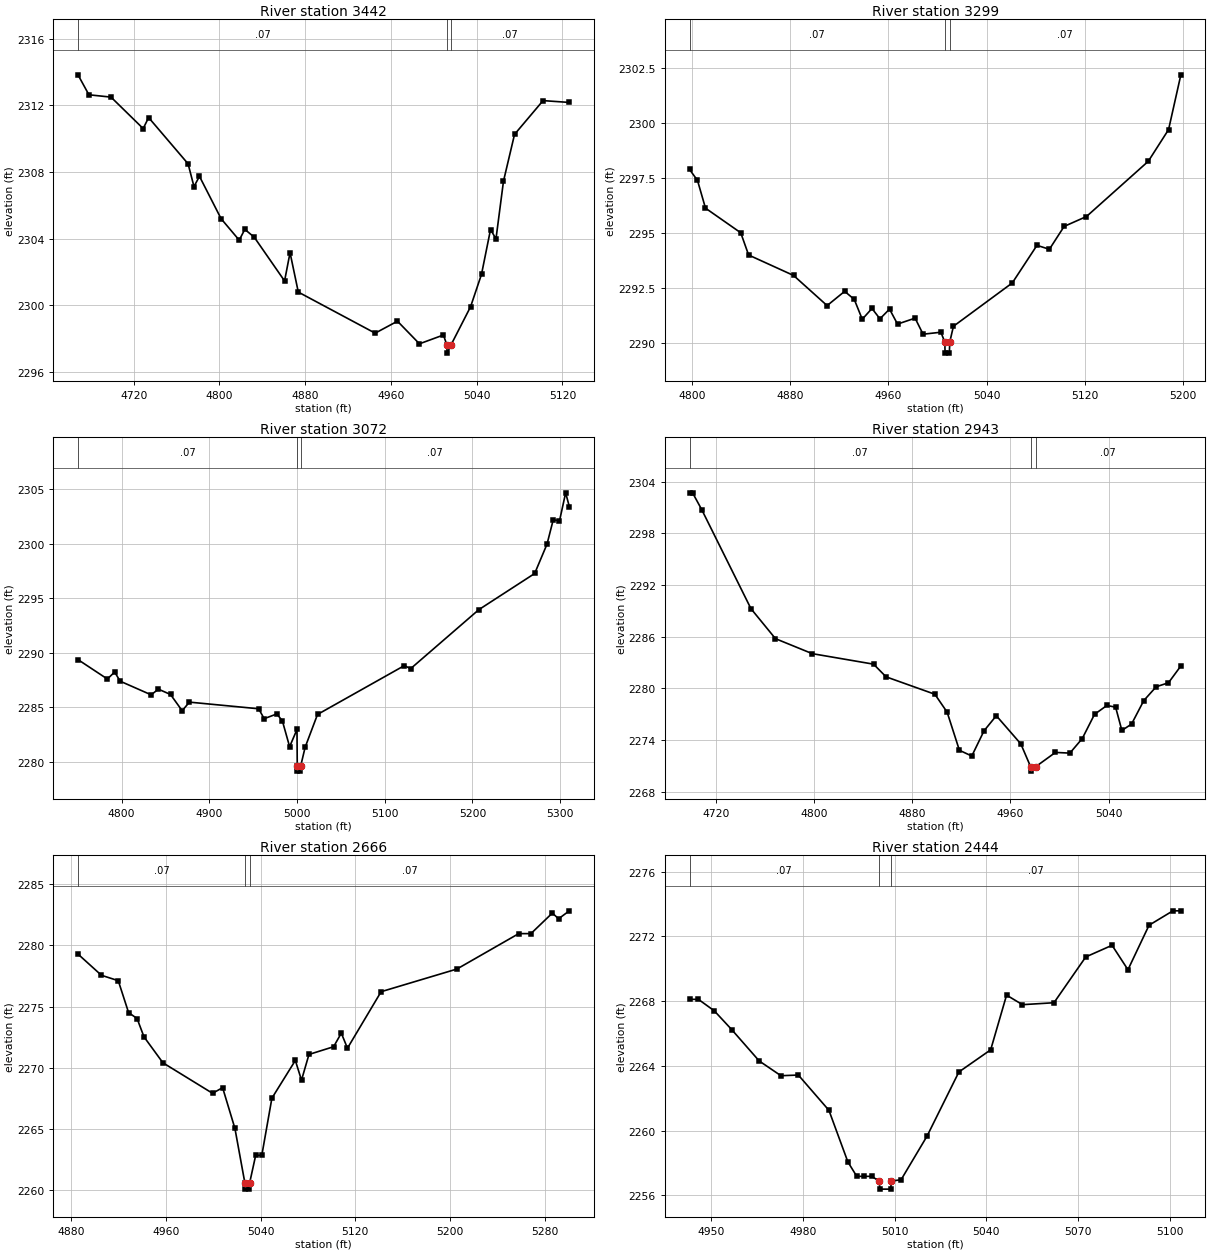
Type RM Length L Ch R = 1,3442,143,143,143
BEGIN DESCRIPTION:
Finn Creek Trib3 6.0
END DESCRIPTION:
XS GIS Cut Line= 3
      1363755.01      6830338.04      1363831.48      6830661.01
      1363954.96      6830687.99
#Sta/Elev= 30
  4668.1 2313.84  4678.3 2312.64  4698.9 2312.50  4728.9 2310.61  4734.0 2311.27
  4770.8 2308.49  4776.3 2307.12  4781.4 2307.74  4801.6 2305.19  4818.5 2303.90
  4823.7 2304.55  4832.5 2304.08  4860.8 2301.45  4865.9 2303.15  4873.6 2300.78
  4945.3 2298.31  4966.1 2299.03  4986.6 2297.67  5009.0 2298.20  5012.1 2297.61
  5012.4 2297.11  5016.1 2297.61  5034.3 2299.90  5044.5 2301.85  5052.9 2304.54
  5058.0 2303.98  5065.0 2307.45  5075.3 2310.26  5101.9 2312.29  5126.4 2312.18
#Mann=3,-1,0
  4668.1    0.07       0  5012.1    0.07       0  5016.1    0.07       0
Bank Sta=5012.1,5016.1
Exp/Cntr=0.3,0.1

Type RM Length L Ch R = 1,3299,227,227,227
BEGIN DESCRIPTION:
Finn Creek Trib3 4325
END DESCRIPTION:
XS GIS Cut Line= 3
      1363598.97      6830645.57      1363754.50      6830774.16
      1363951.36      6830752.04
#Sta/Elev= 30
  4798.2 2297.90  4804.7 2297.40  4811.2 2296.14  4839.9 2295.02  4846.3 2294.01
  4882.9 2293.08  4910.2 2291.71  4924.5 2292.36  4932.3 2291.99  4938.8 2291.09
  4946.7 2291.58  4953.2 2291.11  4961.0 2291.55  4967.5 2290.87  4981.8 2291.14
  4988.3 2290.41  5002.8 2290.50  5006.0 2290.05  5006.2 2289.55  5009.7 2289.55
  5010.0 2290.05  5013.0 2290.77  5060.9 2292.74  5081.0 2294.45  5091.1 2294.27
  5103.1 2295.31  5121.3 2295.76  5171.6 2298.27  5188.1 2299.71  5198.1 2302.20
#Mann=3,-1,0
  4798.2    0.07       0  5006.0    0.07       0  5010.0    0.07       0
Bank Sta=5006,5010
Exp/Cntr=0.3,0.1

Type RM Length L Ch R = 1,3072,129,129,129
BEGIN DESCRIPTION:
Finn Creek Trib3 4326
END DESCRIPTION:
XS GIS Cut Line= 3
      1363601.11      6830834.35      1363799.62      6830985.82
      1364021.05      6830768.14
#Sta/Elev= 30
  4750.3 2289.38  4783.8 2287.60  4792.1 2288.24  4798.4 2287.40  4833.7 2286.15
  4842.0 2286.67  4855.8 2286.18  4869.1 2284.69  4877.3 2285.48  4956.3 2284.87
  4962.6 2283.96  4977.1 2284.40  4983.4 2283.74  4991.6 2281.39  5000.0 2282.97
  5000.3 2279.65  5000.5 2279.15  5004.0 2279.15  5004.3 2279.65  5009.3 2281.34
  5023.4 2284.35  5122.4 2288.83  5129.6 2288.55  5207.3 2293.96  5271.0 2297.28
  5285.1 2299.98  5292.2 2302.22  5299.3 2302.10  5306.3 2304.68  5310.5 2303.42
#Mann=3,-1,0
  4750.3    0.07       0  5000.3    0.07       0  5004.3    0.07       0
Bank Sta=5000.3,5004.3
Exp/Cntr=0.3,0.1

Type RM Length L Ch R = 1,2943,277,277,277
BEGIN DESCRIPTION:
Finn Creek Trib3 5.0
END DESCRIPTION:
XS GIS Cut Line= 3
      1363454.97      6831088.00      1363756.51      6831097.70
      1363855.03      6831088.00
#Sta/Elev= 30
  4698.3 2302.70  4700.8 2302.70  4708.3 2300.74  4748.4 2289.26  4768.4 2285.78
  4798.4 2284.04  4848.4 2282.82  4858.6 2281.35  4898.4 2279.33  4908.4 2277.25
  4918.4 2272.83  4928.5 2272.16  4938.5 2275.09  4948.5 2276.84  4968.5 2273.57
  4976.5 2270.91  4976.7 2270.41  4980.5 2270.91  4996.7 2272.58  5008.5 2272.50
  5018.6 2274.19  5028.6 2277.00  5038.7 2278.03  5045.8 2277.83  5050.9 2275.13
  5058.8 2275.87  5068.8 2278.60  5078.9 2280.20  5088.9 2280.66  5099.0 2282.61
#Mann=3,-1,0
  4698.3    0.07       0  4976.5    0.07       0  4980.5    0.07       0
Bank Sta=4976.5,4980.5
Exp/Cntr=0.3,0.1

Type RM Length L Ch R = 1,2666,222,222,222
BEGIN DESCRIPTION:
Finn Creek Trib3 4327
END DESCRIPTION:
XS GIS Cut Line= 3
      1363557.72      6831287.92      1363657.35      6831343.52
      1363946.14      6831259.71
#Sta/Elev= 30
  4885.9 2279.29  4905.7 2277.56  4919.9 2277.12  4928.6 2274.52  4935.8 2274.03
  4941.6 2272.54  4957.6 2270.42  4999.5 2267.93  5008.0 2268.39  5018.4 2265.06
  5026.8 2260.61  5027.0 2260.11  5030.5 2260.11  5030.8 2260.61  5035.9 2262.86
  5041.1 2262.87  5049.6 2267.53  5069.4 2270.61  5074.6 2269.00  5080.9 2271.10
  5101.7 2271.73  5108.2 2272.84  5113.4 2271.61  5141.8 2276.22  5205.8 2278.07
  5258.0 2280.96  5268.3 2280.96  5286.4 2282.64  5291.6 2282.17  5300.7 2282.82
#Mann=3,-1,0
  4885.9    0.07       0  5026.8    0.07       0  5030.8    0.07       0
Bank Sta=5026.8,5030.8
Exp/Cntr=0.3,0.1

Type RM Length L Ch R = 1,2444,496,496,496
BEGIN DESCRIPTION:
Finn Creek Trib3 4.0
END DESCRIPTION:
XS GIS Cut Line= 3
      1363604.96      6831537.98      1363655.10      6831565.31
      1363755.03      6831537.99
#Sta/Elev= 29
  4942.9 2268.11  4945.8 2268.11  4951.0 2267.40  4956.7 2266.24  4965.7 2264.30
  4972.8 2263.39  4978.5 2263.43  4988.5 2261.25  4994.7 2258.06  4997.6 2257.17
  5000.0 2257.17  5002.5 2257.17  5004.9 2256.88  5005.2 2256.38  5008.7 2256.38
  5008.9 2256.88  5012.1 2256.96  5020.6 2259.66  5031.0 2263.62  5041.4 2264.99
  5046.6 2268.37  5051.8 2267.78  5062.1 2267.90  5072.5 2270.73  5081.1 2271.45
  5086.3 2269.94  5093.2 2272.69  5101.0 2273.58  5103.6 2273.58
#Mann=3,-1,0
  4942.9    0.07       0  5004.9    0.07       0  5008.9    0.07       0
Bank Sta=5004.9,5008.9
Exp/Cntr=0.3,0.1

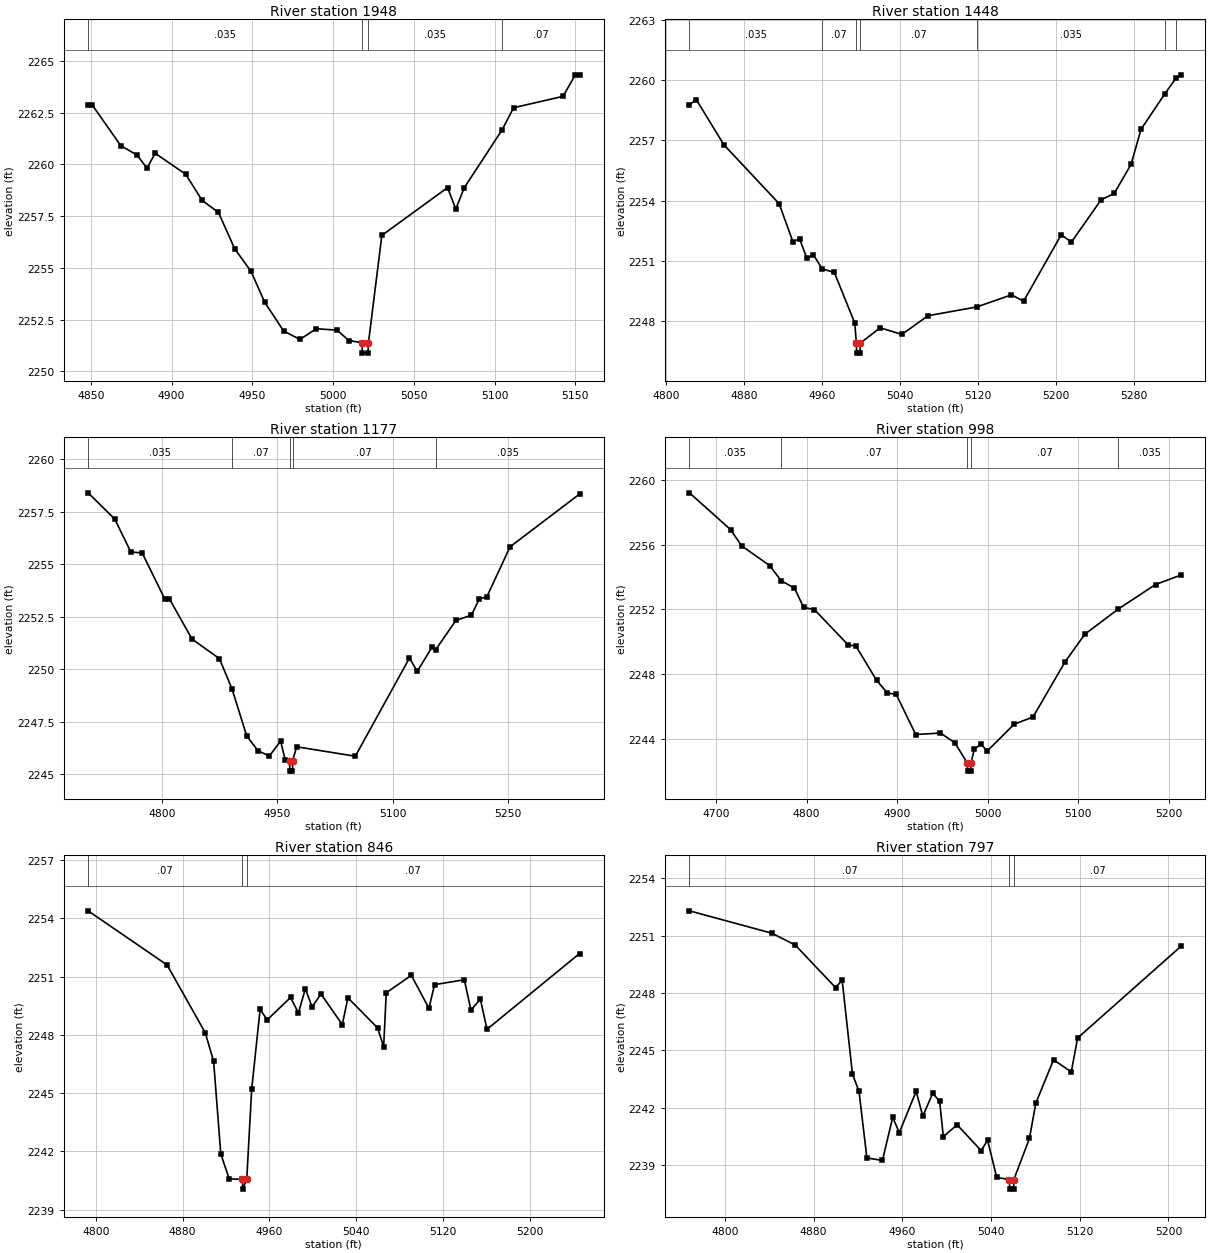
Type RM Length L Ch R = 1,1948,500,500,500
BEGIN DESCRIPTION:
Finn Creek Trib3 3.0
END DESCRIPTION:
XS GIS Cut Line= 3
      1363355.00      6831988.00      1363505.35      6832008.15
      1363655.00      6832038.00
#Sta/Elev= 30
  4848.3 2262.88  4850.8 2262.88  4868.5 2260.91  4878.6 2260.45  4884.8 2259.82
  4889.8 2260.54  4908.8 2259.52  4918.9 2258.26  4929.0 2257.68  4939.1 2255.92
  4949.2 2254.83  4957.7 2253.33  4969.4 2251.95  4979.5 2251.54  4989.6 2252.06
  5002.4 2251.99  5009.8 2251.49  5017.9 2251.38  5018.1 2250.88  5021.6 2250.88
  5021.9 2251.38  5030.2 2256.57  5070.9 2258.88  5076.0 2257.84  5081.2 2258.87
  5104.6 2261.66  5111.8 2262.74  5142.4 2263.29  5150.0 2264.33  5152.6 2264.33
#Mann=4,-1,0
  4848.3   0.035       0  5017.9   0.035       0  5021.9   0.035       0
  5104.6    0.07       0
Bank Sta=5017.9,5021.9
Exp/Cntr=0.3,0.1

Type RM Length L Ch R = 1,1448,271,271,271
BEGIN DESCRIPTION:
Finn Creek Trib3 2.0
END DESCRIPTION:
XS GIS Cut Line= 3
      1363155.00      6832288.00      1363284.08      6832407.93
      1363604.95      6832338.01
#Sta/Elev= 30
  4823.8 2258.77  4830.9 2259.01  4859.2 2256.77  4915.9 2253.84  4930.1 2251.94
  4936.9 2252.10  4944.3 2251.13  4951.1 2251.30  4960.1 2250.60  4972.6 2250.42
  4993.6 2247.90  4995.2 2246.91  4995.5 2246.41  4999.0 2246.41  4999.2 2246.91
  5019.7 2247.67  5041.9 2247.34  5068.8 2248.27  5119.1 2248.71  5154.5 2249.31
  5166.9 2248.99  5205.6 2252.30  5216.0 2251.93  5246.6 2254.04  5260.0 2254.35
  5277.3 2255.80  5287.5 2257.54  5312.0 2259.31  5323.5 2260.09  5328.4 2260.25
#Mann=7,-1,0
  4823.8   0.035       0  4960.1    0.07       0  4995.2    0.07       0
  4999.2    0.07       0  5119.1   0.035       0  5312.0    0.07       0
  5323.5   0.035       0
Bank Sta=4995.2,4999.2
Exp/Cntr=0.3,0.1

Type RM Length L Ch R = 1,1177,179,179,179
BEGIN DESCRIPTION:
Finn Creek Trib3 4323
END DESCRIPTION:
XS GIS Cut Line= 3
      1363030.38      6832383.86      1363204.03      6832624.07
      1363544.66      6832665.95
#Sta/Elev= 30
  4703.6 2258.41  4738.3 2257.16  4759.2 2255.59  4773.9 2255.55  4803.3 2253.36
  4809.5 2253.35  4838.9 2251.44  4874.5 2250.51  4890.9 2249.07  4910.0 2246.83
  4924.7 2246.12  4939.5 2245.87  4954.2 2246.58  4960.3 2245.66  4965.8 2245.65
  4966.1 2245.15  4969.6 2245.15  4969.8 2245.65  4975.0 2246.31  5051.4 2245.86
  5121.9 2250.54  5132.0 2249.90  5151.1 2251.05  5156.1 2250.94  5182.3 2252.33
  5202.5 2252.58  5212.6 2253.34  5222.6 2253.46  5252.9 2255.84  5343.2 2258.35
#Mann=5,-1,0
  4703.6   0.035       0  4890.9    0.07       0  4965.8    0.07       0
  4969.8    0.07       0  5156.1   0.035       0
Bank Sta=4965.8,4969.8
Exp/Cntr=0.3,0.1

Type RM Length L Ch R = 1,998,152,152,152
BEGIN DESCRIPTION:
Finn Creek Trib3 1.0
END DESCRIPTION:
XS GIS Cut Line= 3
      1362904.99      6832437.98      1363068.16      6832724.25
      1363205.00      6832888.00
#Sta/Elev= 30
  4670.5 2259.19  4715.9 2256.92  4728.1 2255.92  4759.1 2254.70  4771.9 2253.76
  4786.5 2253.31  4796.6 2252.12  4808.6 2251.98  4845.5 2249.82  4854.7 2249.71
  4877.3 2247.61  4889.2 2246.83  4898.9 2246.75  4920.5 2244.27  4947.8 2244.36
  4963.7 2243.76  4977.5 2242.51  4977.8 2242.01  4981.3 2242.01  4981.5 2242.51
  4985.3 2243.37  4992.8 2243.68  4999.3 2243.24  5029.3 2244.91  5050.1 2245.35
  5085.2 2248.73  5107.3 2250.46  5144.4 2252.02  5185.4 2253.53  5213.4 2254.11
#Mann=5,-1,0
  4670.5   0.035       0  4771.9    0.07       0  4977.5    0.07       0
  4981.5    0.07       0  5144.4   0.035       0
Bank Sta=4977.5,4981.5
Exp/Cntr=0.3,0.1

Type RM Length L Ch R = 1,846,49,49,49
BEGIN DESCRIPTION:
Finn Creek Trib3 4320
END DESCRIPTION:
XS GIS Cut Line= 6
      1362793.83      6832606.28      1362906.67      6832737.57
      1362927.81      6832764.05      1362994.56      6832784.23
      1363058.58      6832799.42      1363148.30      6832863.19
#Sta/Elev= 30
  4793.0 2254.39  4865.8 2251.60  4900.9 2248.11  4908.6 2246.64  4915.2 2241.88
  4922.9 2240.59  4935.1 2240.56  4935.4 2240.06  4939.1 2240.56  4943.7 2245.23
  4951.4 2249.31  4958.0 2248.78  4979.5 2249.93  4986.7 2249.13  4993.1 2250.38
  4999.3 2249.44  5007.5 2250.11  5027.1 2248.53  5032.3 2249.91  5059.7 2248.36
  5065.2 2247.38  5067.6 2250.17  5090.7 2251.07  5106.9 2249.37  5112.1 2250.59
  5139.5 2250.84  5145.6 2249.28  5154.3 2249.84  5160.4 2248.29  5245.6 2252.19
#Mann=3,-1,0
  4793.0    0.07       0  4935.1    0.07       0  4939.1    0.07       0
Bank Sta=4935.1,4939.1
Exp/Cntr=0.3,0.1

Type RM Length L Ch R = 1,797,298,298,298
BEGIN DESCRIPTION:
Finn Creek Trib3 4319
END DESCRIPTION:
XS GIS Cut Line= 3
      1362710.27      6832681.14      1362905.50      6832806.29
      1363090.04      6832909.01
#Sta/Elev= 30
  4768.1 2252.29  4842.4 2251.12  4863.5 2250.50  4899.8 2248.28  4905.8 2248.66
  4915.1 2243.75  4921.0 2242.85  4928.1 2239.37  4942.1 2239.24  4951.4 2241.50
  4957.3 2240.69  4972.5 2242.85  4978.5 2241.56  4987.5 2242.75  4993.7 2242.33
  4997.0 2240.49  5009.5 2241.10  5031.2 2239.75  5036.9 2240.30  5045.2 2238.35
  5056.6 2238.24  5056.9 2237.74  5060.4 2237.74  5060.6 2238.24  5074.7 2240.39
  5080.4 2242.23  5096.4 2244.50  5112.4 2243.87  5118.1 2245.64  5211.2 2250.43
#Mann=3,-1,0
  4768.1    0.07       0  5056.6    0.07       0  5060.6    0.07       0
Bank Sta=5056.6,5060.6
Exp/Cntr=0.3,0.1

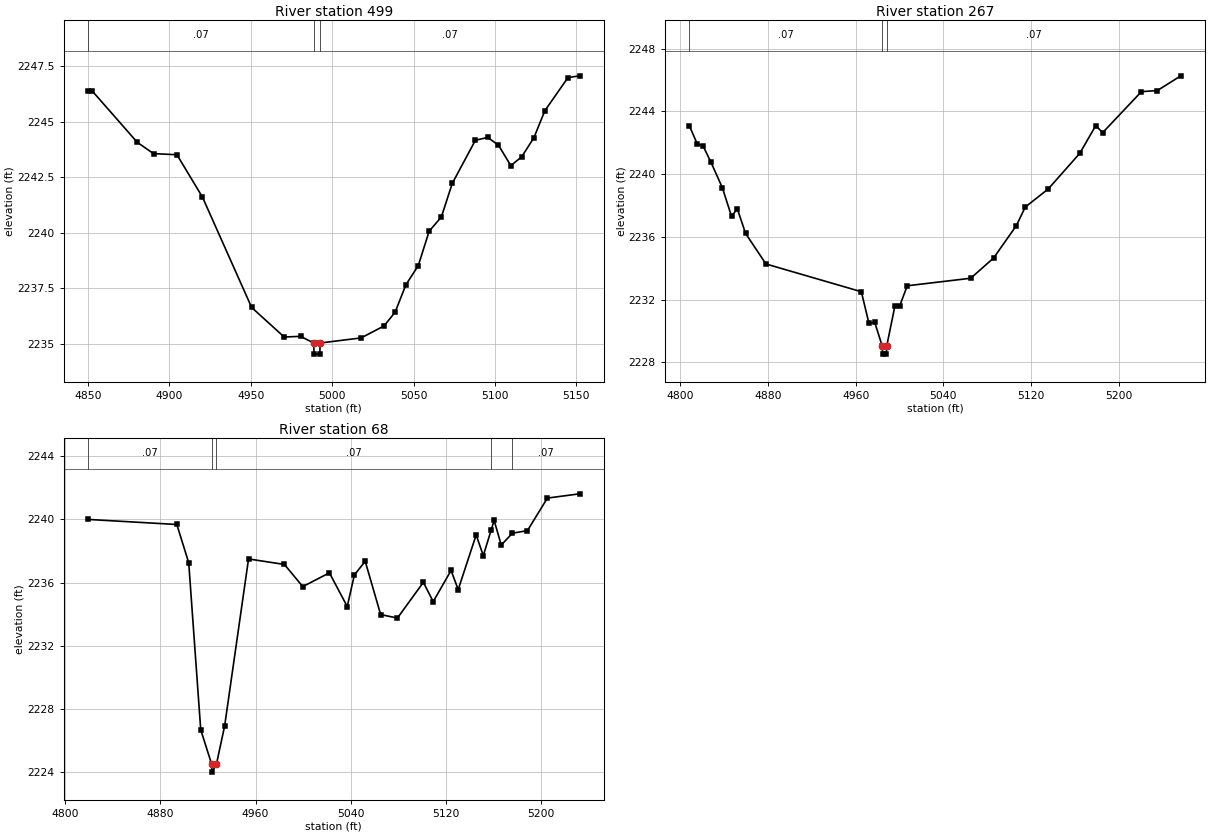
Type RM Length L Ch R = 1,499,232,232,232
BEGIN DESCRIPTION:
Finn Creek Trib3 1756
END DESCRIPTION:
XS GIS Cut Line= 3
      1362705.00      6832837.98      1362691.09      6832987.33
      1362804.98      6833087.99
#Sta/Elev= 30
  4850.0 2246.38  4852.5 2246.38  4880.2 2244.07  4890.2 2243.56  4904.6 2243.51
  4920.3 2241.60  4950.5 2236.64  4970.5 2235.31  4980.6 2235.34  4988.6 2235.04
  4988.9 2234.54  4992.4 2234.54  4992.6 2235.04  5017.8 2235.27  5031.9 2235.81
  5038.7 2236.43  5045.3 2237.66  5052.9 2238.52  5059.6 2240.07  5067.1 2240.71
  5073.8 2242.22  5088.0 2244.16  5095.6 2244.29  5102.2 2243.94  5109.8 2243.02
  5116.5 2243.42  5124.0 2244.28  5130.7 2245.49  5144.9 2246.98  5152.0 2247.06
#Mann=3,-1,0
  4850.0    0.07       0  4988.6    0.07       0  4992.6    0.07       0
Bank Sta=4988.6,4992.6
Exp/Cntr=0.3,0.1

Type RM Length L Ch R = 1,267,199,199,199
BEGIN DESCRIPTION:
Finn Creek Trib3 4322
END DESCRIPTION:
XS GIS Cut Line= 3
      1362533.42      6832839.54      1362471.47      6833021.06
      1362674.51      6833178.14
#Sta/Elev= 30
  4808.2 2243.07  4815.3 2241.93  4820.6 2241.80  4827.7 2240.78  4838.3 2239.12
  4846.6 2237.31  4851.9 2237.79  4859.4 2236.22  4878.0 2234.27  4965.1 2232.50
  4972.0 2230.49  4977.3 2230.55  4984.2 2229.02  4984.4 2228.52  4987.9 2228.52
  4988.2 2229.02  4995.7 2231.58  5000.0 2231.58  5007.0 2232.88  5064.9 2233.36
  5085.8 2234.65  5106.6 2236.72  5114.7 2237.90  5135.6 2239.05  5164.5 2241.33
  5179.0 2243.09  5185.4 2242.65  5220.7 2245.26  5235.2 2245.33  5256.7 2246.27
#Mann=3,-1,0
  4808.2    0.07       0  4984.2    0.07       0  4988.2    0.07       0
Bank Sta=4984.2,4988.2
Exp/Cntr=0.3,0.1

Type RM Length L Ch R = 1,68,0,0,0
BEGIN DESCRIPTION:
Finn Creek Trib3 4321
END DESCRIPTION:
XS GIS Cut Line= 4
      1362299.04      6832893.85      1362318.47      6833073.60
      1362411.88      6833215.00      1362440.03      6833271.29
#Sta/Elev= 30
  4819.2 2240.00  4893.8 2239.68  4903.8 2237.26  4913.9 2226.69  4923.1 2224.51
  4923.3 2224.01  4927.1 2224.51  4934.0 2226.93  4954.1 2237.50  4984.3 2237.15
  4999.7 2235.75  5022.1 2236.62  5037.1 2234.49  5043.1 2236.49  5052.2 2237.35
  5065.2 2233.98  5079.3 2233.76  5101.1 2236.02  5109.4 2234.80  5124.4 2236.77
  5130.4 2235.56  5145.5 2239.02  5151.5 2237.71  5158.0 2239.30  5160.6 2239.94
  5166.6 2238.38  5176.0 2239.13  5188.6 2239.29  5205.4 2241.35  5232.4 2241.62
#Mann=5,-1,0
  4819.2    0.07       0  4923.1    0.07       0  4927.1    0.07       0
  5158.0    0.16       0  5176.0    0.07       0
Bank Sta=4923.1,4927.1
Exp/Cntr=0.3,0.1

Chan Stop Cuts=-1