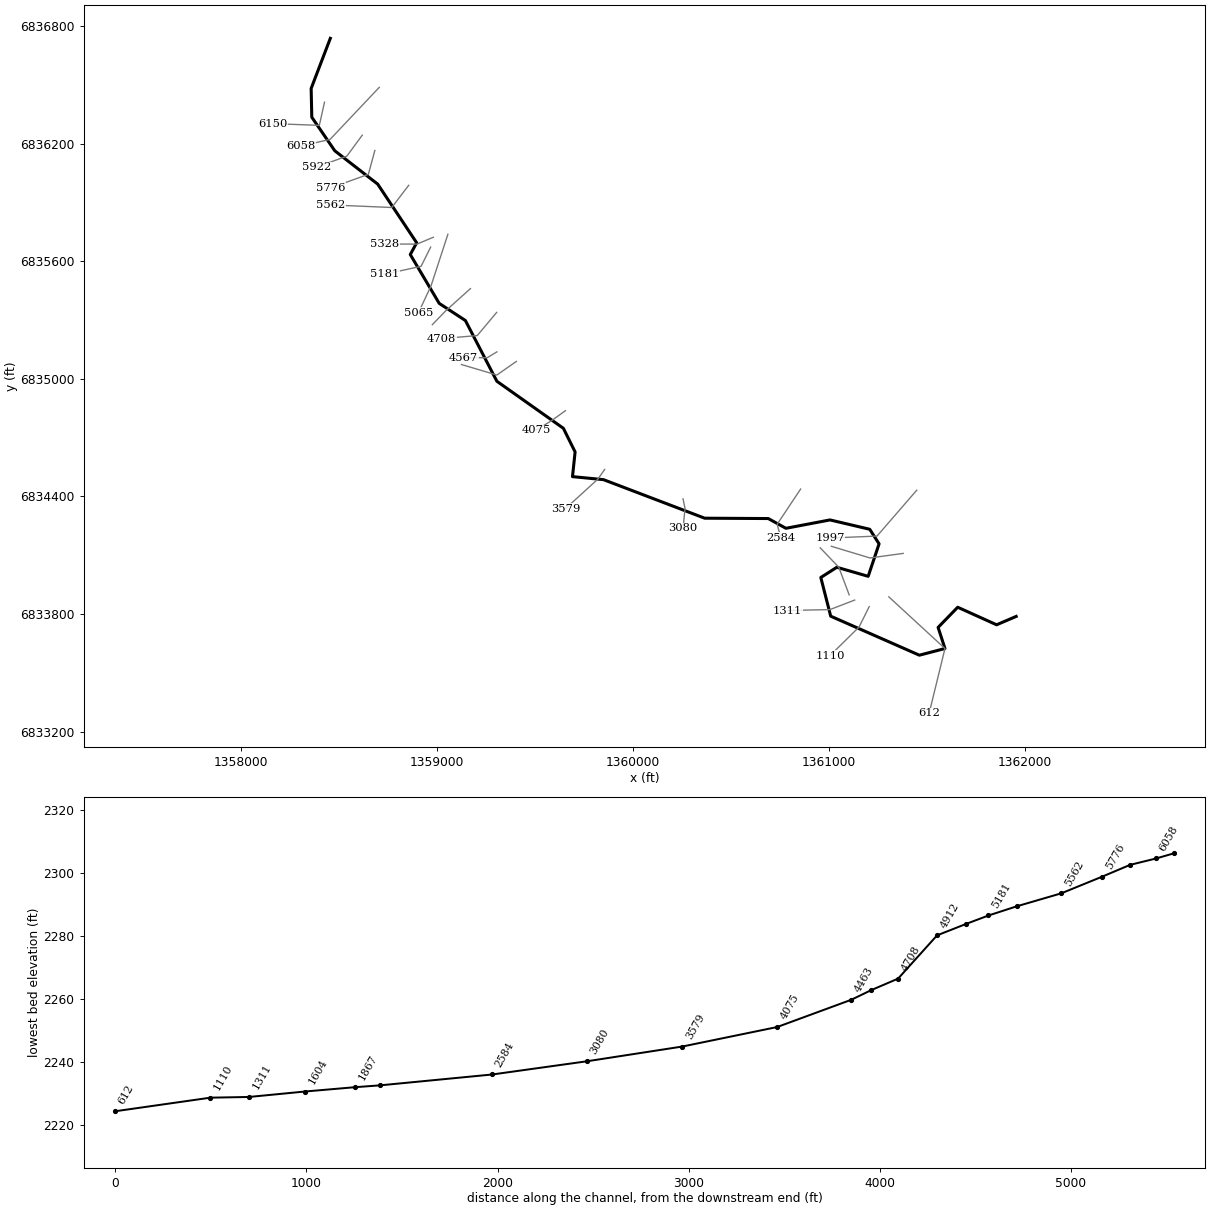
--- Finn Creek Trib4.prj (project) ---

Proj Title=Finn Creek Trib4 Base Level Engineering
Current Plan=p01
Default Exp/Contr=0.3,0.1
English Units
Geom File=g01
Flow File=f01
Plan File=p01
Y Axis Title=Elevation
X Axis Title(PF)=Main Channel Distance
X Axis Title(XS)=Station
BEGIN DESCRIPTION:
Finn Creek Trib4
END DESCRIPTION:
DSS Export Rating Curves= 0
DSS Export Rating Curve Sorted= 0
DSS Export Volume Flow Curves= 0
DXF OffsetX= 0
DXF OffsetY= 0
DXF ScaleX= 1
DXF ScaleY= 10

--- Finn Creek Trib4.p01 (plan) ---

Plan Title=Multiple Run
Short Identifier=Multiple
Geom File=g01
Flow File=f01
Subcritical Flow
K Sum by GR= 0
Std Step Tol= 0.01
Critical Tol= 0.01
Num of Std Step Trials= 20
Max Error Tol= 0.3
Flow Tol Ratio= 0.001
Split Flow NTrial= 30
Split Flow Tol= 0.02
Split Flow Ratio= 0.02
Log Output Level= 0
Friction Slope Method= 1
Unsteady Friction Slope Method= 2
Unsteady Bridges Friction Slope Method= 1
Parabolic Critical Depth
Global Vel Dist=  1 , 1 , 1
Global Log Level= 0
CheckData=True
Encroach Param= -1, 0, 0, 0
BEGIN DESCRIPTION:
Multiple Run
END DESCRIPTION:

--- Finn Creek Trib4.f01 (steady flow) ---

Flow Title=Multiple
Number of Profiles=7
Profile Names=10-year,25-year,50-year,1pct_min,100-year,1pct_plu,500-year
River Rch & RM= Finn Creek Trib4,Reach-1,6150
      50      64      75      44      88     176     122
River Rch & RM= Finn Creek Trib4,Reach-1,4463
     193     271     336     207     413     825     635
River Rch & RM= Finn Creek Trib4,Reach-1,4075
     258     369     463     289     576    1150     906
Boundary for River Rch & Prof#=Finn Creek Trib4,Reach-1,1
Up Type=0
Dn Type=3
Dn Slope=0.005
Boundary for River Rch & Prof#=Finn Creek Trib4,Reach-1,2
Up Type=0
Dn Type=3
Dn Slope=0.005
Boundary for River Rch & Prof#=Finn Creek Trib4,Reach-1,3
Up Type=0
Dn Type=3
Dn Slope=0.005
Boundary for River Rch & Prof#=Finn Creek Trib4,Reach-1,4
Up Type=0
Dn Type=3
Dn Slope=0.005
Boundary for River Rch & Prof#=Finn Creek Trib4,Reach-1,5
Up Type=0
Dn Type=3
Dn Slope=0.005
Boundary for River Rch & Prof#=Finn Creek Trib4,Reach-1,6
Up Type=0
Dn Type=3
Dn Slope=0.005
Boundary for River Rch & Prof#=Finn Creek Trib4,Reach-1,7
Up Type=0
Dn Type=3
Dn Slope=0.005

--- Finn Creek Trib4.g01 (geometry) ---

Geom Title=Existing Conditions

River Reach=Finn Creek Trib4,Reach-1
Reach XY= 30
      1358455.00      6836738.00      1358357.23      6836482.07
      1358360.47      6836335.56      1358477.86      6836164.16
      1358696.84      6835994.05      1358895.68      6835694.66
      1358863.02      6835634.67      1359010.73      6835385.45
      1359144.35      6835297.99      1359305.00      6834988.00
      1359644.37      6834748.00      1359704.20      6834627.30
      1359690.87      6834501.36      1359849.14      6834485.92
      1360365.50      6834289.22      1360689.79      6834287.46
      1360780.04      6834237.69      1361004.99      6834280.41
      1361207.77      6834232.64      1361255.39      6834158.28
      1361199.76      6833992.62      1361039.85      6834038.79
      1360958.03      6833986.61      1361008.51      6833789.25
      1361460.97      6833590.14      1361591.63      6833624.19
      1361556.65      6833731.96      1361656.62      6833834.88
      1361855.03      6833745.28      1361955.00      6833788.00

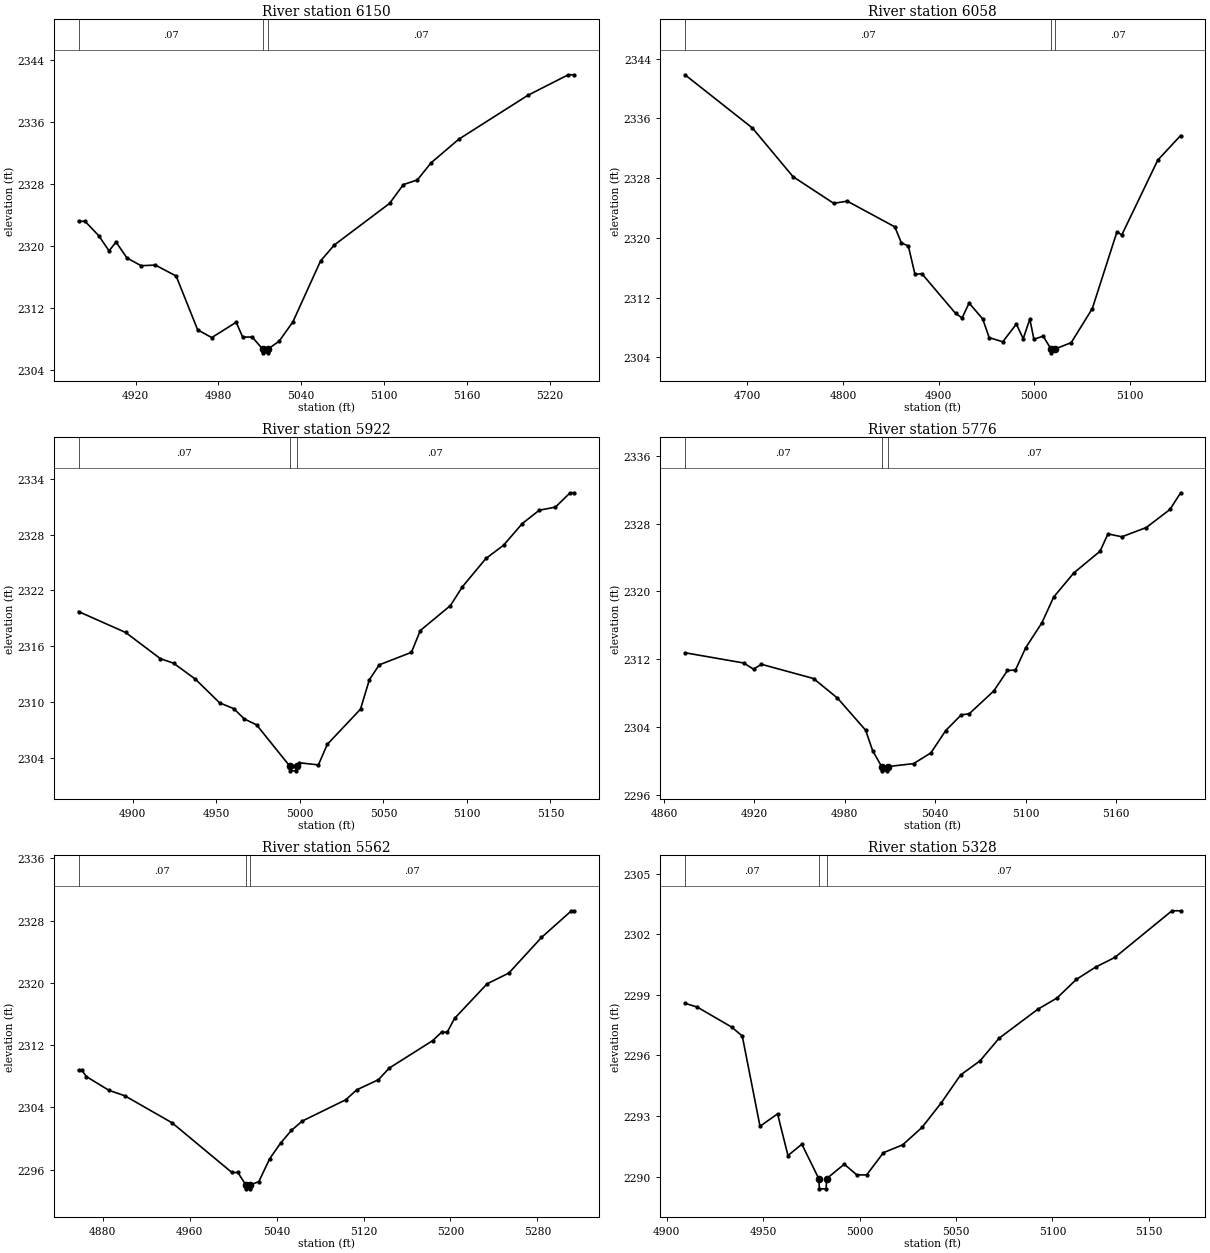
Type RM Length L Ch R = 1,6150,92,92,92
BEGIN DESCRIPTION:
Finn Creek Trib4 4328
END DESCRIPTION:
XS GIS Cut Line= 3
      1358425.33      6836412.23      1358398.96      6836293.83
      1358161.44      6836302.85
#Sta/Elev= 30
  4878.7 2323.21  4883.4 2323.21  4893.3 2321.36  4900.8 2319.39  4905.9 2320.52
  4913.8 2318.47  4924.0 2317.47  4934.3 2317.55  4949.4 2316.14  4965.0 2309.18
  4975.2 2308.18  4992.9 2310.16  4997.6 2308.25  5004.5 2308.25  5012.0 2306.71
  5012.2 2306.21  5015.7 2306.21  5016.0 2306.71  5024.0 2307.71  5034.0 2310.22
  5054.0 2318.08  5064.0 2320.15  5104.0 2325.52  5114.0 2327.95  5124.1 2328.55
  5134.1 2330.77  5154.1 2333.81  5204.1 2339.48  5233.4 2342.14  5237.7 2342.14
#Mann=3,-1,0
  4878.7    0.07       0  5012.0    0.07       0  5016.0    0.07       0
Bank Sta=5012,5016
Exp/Cntr=0.3,0.1

Type RM Length L Ch R = 1,6058,136,136,136
BEGIN DESCRIPTION:
Finn Creek Trib4 11.0
END DESCRIPTION:
XS GIS Cut Line= 3
      1358704.97      6836487.97      1358454.10      6836222.58
      1358304.96      6836187.99
#Sta/Elev= 30
  4634.8 2341.85  4705.4 2334.71  4747.8 2328.20  4790.3 2324.63  4804.5 2324.92
  4854.2 2321.48  4861.1 2319.33  4868.4 2318.91  4875.3 2315.11  4882.5 2315.21
  4917.7 2309.89  4924.6 2309.28  4931.9 2311.27  4946.1 2309.15  4952.9 2306.64
  4967.1 2306.08  4981.3 2308.45  4988.5 2306.50  4995.4 2309.12  4999.7 2306.41
  5009.3 2306.84  5017.6 2305.10  5017.9 2304.60  5021.6 2305.10  5038.7 2305.97
  5060.7 2310.52  5086.5 2320.81  5091.6 2320.40  5129.2 2330.42  5153.1 2333.71
#Mann=3,-1,0
  4634.8    0.07       0  5017.6    0.07       0  5021.6    0.07       0
Bank Sta=5017.6,5021.6
Exp/Cntr=0.3,0.1

Type RM Length L Ch R = 1,5922,146,146,146
BEGIN DESCRIPTION:
Finn Creek Trib4 4329
END DESCRIPTION:
XS GIS Cut Line= 3
      1358618.07      6836243.86      1358539.58      6836137.10
      1358385.40      6836080.62
#Sta/Elev= 30
  4867.5 2319.72  4895.7 2317.47  4916.5 2314.65  4924.4 2314.16  4937.4 2312.45
  4952.0 2309.89  4960.5 2309.26  4966.7 2308.16  4974.1 2307.52  4994.0 2303.07
  4994.2 2302.57  4997.7 2302.57  4998.0 2303.07  4999.6 2303.44  5011.1 2303.21
  5016.4 2305.42  5036.3 2309.21  5041.6 2312.38  5047.5 2313.98  5066.8 2315.33
  5072.1 2317.68  5090.1 2320.36  5097.3 2322.39  5111.4 2325.44  5122.0 2326.87
  5133.1 2329.19  5143.3 2330.63  5153.0 2330.97  5161.8 2332.51  5164.2 2332.51
#Mann=3,-1,0
  4867.5    0.07       0  4994.0    0.07       0  4998.0    0.07       0
Bank Sta=4994,4998
Exp/Cntr=0.3,0.1

Type RM Length L Ch R = 1,5776,214,214,214
BEGIN DESCRIPTION:
Finn Creek Trib4 4330
END DESCRIPTION:
XS GIS Cut Line= 3
      1358682.27      6836165.66      1358649.22      6836044.07
      1358458.32      6835975.35
#Sta/Elev= 30
  4874.0 2312.76  4913.0 2311.55  4919.5 2310.82  4924.7 2311.40  4959.3 2309.72
  4975.2 2307.41  4993.9 2303.62  4998.5 2301.22  5004.5 2299.33  5004.7 2298.83
  5008.2 2298.83  5008.5 2299.33  5025.7 2299.68  5037.2 2300.95  5047.0 2303.58
  5057.3 2305.43  5062.6 2305.56  5078.9 2308.25  5088.0 2310.67  5093.3 2310.72
  5100.1 2313.35  5110.8 2316.28  5118.7 2319.34  5132.0 2322.17  5149.4 2324.73
  5154.7 2326.78  5163.9 2326.44  5180.1 2327.53  5195.8 2329.66  5202.9 2331.63
#Mann=3,-1,0
  4874.0    0.07       0  5004.5    0.07       0  5008.5    0.07       0
Bank Sta=5004.5,5008.5
Exp/Cntr=0.3,0.1

Type RM Length L Ch R = 1,5562,234,234,234
BEGIN DESCRIPTION:
Finn Creek Trib4 10.0
END DESCRIPTION:
XS GIS Cut Line= 3
      1358854.97      6835987.96      1358768.58      6835874.77
      1358454.96      6835888.00
#Sta/Elev= 30
  4857.6 2308.77  4860.7 2308.77  4864.8 2307.96  4885.6 2306.19  4900.2 2305.49
  4943.8 2302.01  4998.8 2295.63  5004.3 2295.63  5011.6 2294.03  5011.8 2293.53
  5015.3 2293.53  5015.6 2294.03  5023.6 2294.46  5033.6 2297.40  5043.6 2299.40
  5053.6 2301.04  5063.6 2302.24  5103.7 2304.98  5113.7 2306.25  5133.7 2307.55
  5143.7 2309.05  5183.7 2312.58  5192.0 2313.68  5197.0 2313.65  5203.8 2315.43
  5233.8 2319.88  5253.8 2321.26  5283.8 2325.83  5311.4 2329.26  5313.9 2329.26
#Mann=3,-1,0
  4857.6    0.07       0  5011.6    0.07       0  5015.6    0.07       0
Bank Sta=5011.6,5015.6
Exp/Cntr=0.3,0.1

Type RM Length L Ch R = 1,5328,147,147,147
BEGIN DESCRIPTION:
Finn Creek Trib4 4333
END DESCRIPTION:
XS GIS Cut Line= 3
      1358980.89      6835722.99      1358897.43      6835688.00
      1358730.93      6835688.26
#Sta/Elev= 29
  4909.5 2298.58  4915.9 2298.39  4933.7 2297.40  4939.2 2296.96  4948.4 2292.49
  4957.5 2293.10  4962.9 2291.04  4970.1 2291.60  4978.9 2289.89  4979.2 2289.39
  4982.7 2289.39  4982.9 2289.89  4992.1 2290.61  4998.6 2290.08  5003.7 2290.08
  5012.4 2291.18  5022.4 2291.57  5032.4 2292.43  5042.4 2293.65  5052.4 2295.03
  5062.4 2295.72  5072.4 2296.85  5092.4 2298.28  5102.4 2298.84  5112.4 2299.76
  5122.4 2300.37  5132.4 2300.85  5162.0 2303.16  5166.5 2303.16
#Mann=3,-1,0
  4909.5    0.07       0  4978.9    0.07       0  4982.9    0.07       0
Bank Sta=4978.9,4982.9
Exp/Cntr=0.3,0.1

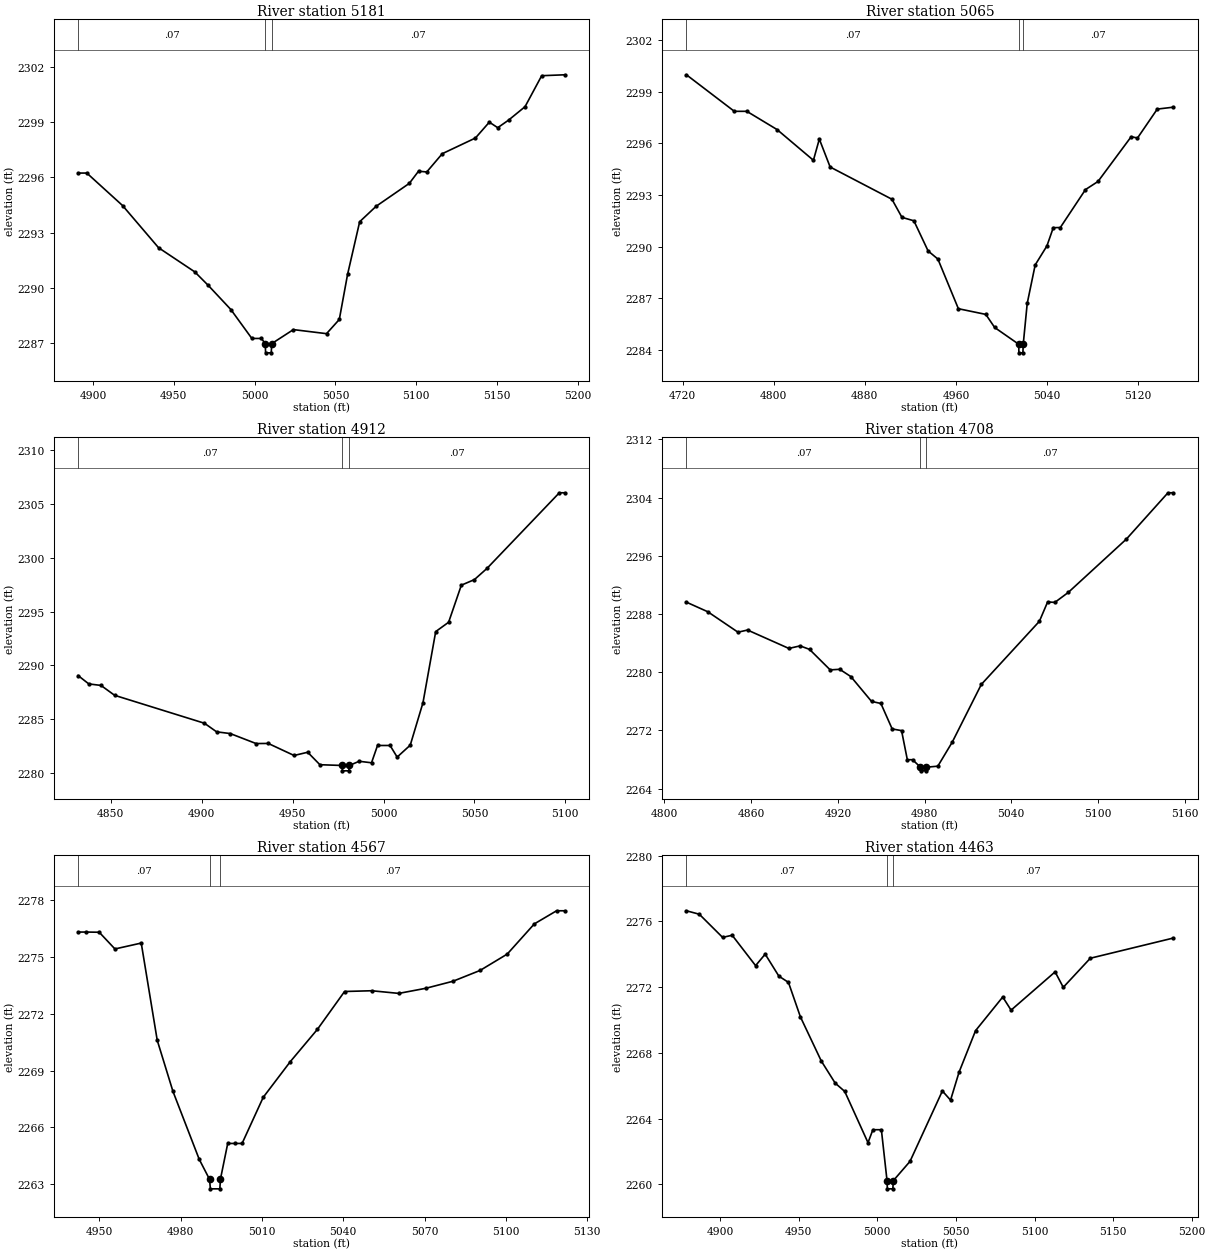
Type RM Length L Ch R = 1,5181,116,116,116
BEGIN DESCRIPTION:
Finn Creek Trib4 4332
END DESCRIPTION:
XS GIS Cut Line= 3
      1358967.00      6835672.63      1358918.45      6835574.81
      1358730.90      6835533.75
#Sta/Elev= 30
  4890.8 2296.24  4896.2 2296.24  4918.3 2294.48  4940.6 2292.19  4963.0 2290.88
  4971.3 2290.15  4985.3 2288.84  4998.3 2287.27  5004.2 2287.27  5006.6 2286.99
  5006.8 2286.49  5010.3 2286.49  5010.6 2286.99  5024.0 2287.75  5044.5 2287.53
  5052.4 2288.30  5057.5 2290.74  5065.0 2293.60  5075.2 2294.44  5095.7 2295.68
  5101.4 2296.34  5106.5 2296.30  5116.1 2297.29  5136.6 2298.14  5145.2 2299.00
  5150.4 2298.70  5157.1 2299.11  5167.3 2299.84  5177.6 2301.52  5192.0 2301.57
#Mann=3,-1,0
  4890.8    0.07       0  5006.6    0.07       0  5010.6    0.07       0
Bank Sta=5006.6,5010.6
Exp/Cntr=0.3,0.1

Type RM Length L Ch R = 1,5065,153,153,153
BEGIN DESCRIPTION:
Finn Creek Trib4 9.0
END DESCRIPTION:
XS GIS Cut Line= 3
      1359055.01      6835738.02      1358968.98      6835474.93
      1358905.02      6835338.04
#Sta/Elev= 30
  4723.2 2299.97  4765.3 2297.85  4776.3 2297.85  4802.9 2296.79  4834.8 2295.01
  4840.0 2296.24  4849.5 2294.62  4903.8 2292.75  4912.6 2291.70  4923.1 2291.50
  4935.6 2289.75  4944.2 2289.28  4962.2 2286.40  4986.3 2286.07  4994.1 2285.31
  5015.2 2284.34  5015.4 2283.84  5018.9 2283.84  5019.2 2284.34  5022.7 2286.71
  5029.7 2288.94  5040.0 2290.04  5045.6 2291.10  5051.8 2291.11  5073.9 2293.31
  5084.9 2293.78  5114.1 2296.38  5119.6 2296.30  5137.0 2297.98  5151.1 2298.09
#Mann=3,-1,0
  4723.2    0.07       0  5015.2    0.07       0  5019.2    0.07       0
Bank Sta=5015.2,5019.2
Exp/Cntr=0.3,0.1

Type RM Length L Ch R = 1,4912,204,204,204
BEGIN DESCRIPTION:
Finn Creek Trib4 4334
END DESCRIPTION:
XS GIS Cut Line= 3
      1359170.10      6835460.81      1359045.02      6835348.65
      1358975.72      6835276.84
#Sta/Elev= 30
  4832.0 2289.05  4837.9 2288.27  4844.6 2288.13  4852.1 2287.21  4901.5 2284.61
  4908.2 2283.81  4915.7 2283.65  4929.9 2282.72  4936.6 2282.73  4950.8 2281.61
  4958.3 2281.91  4965.0 2280.75  4977.2 2280.68  4977.4 2280.18  4980.9 2280.18
  4981.2 2280.68  4986.6 2281.07  4993.4 2280.93  4996.7 2282.54  5003.6 2282.54
  5007.5 2281.46  5014.7 2282.57  5021.7 2286.52  5028.7 2293.14  5035.8 2294.01
  5042.8 2297.46  5050.0 2297.98  5056.9 2299.02  5096.7 2306.06  5099.8 2306.06
#Mann=3,-1,0
  4832.0    0.07       0  4977.2    0.07       0  4981.2    0.07       0
Bank Sta=4977.2,4981.2
Exp/Cntr=0.3,0.1

Type RM Length L Ch R = 1,4708,141,141,141
BEGIN DESCRIPTION:
Finn Creek Trib4 4331
END DESCRIPTION:
XS GIS Cut Line= 3
      1359303.83      6835339.34      1359204.85      6835221.25
      1359022.60      6835205.63
#Sta/Elev= 30
  4815.2 2289.63  4830.0 2288.31  4850.9 2285.50  4857.5 2285.80  4886.1 2283.27
  4893.9 2283.62  4900.4 2283.14  4914.7 2280.32  4921.3 2280.40  4929.0 2279.40
  4943.3 2275.99  4949.8 2275.70  4957.6 2272.20  4964.1 2271.97  4968.1 2267.97
  4971.7 2267.97  4977.2 2266.94  4977.4 2266.44  4980.9 2266.44  4981.2 2266.94
  4989.2 2267.08  4999.2 2270.39  5019.3 2278.32  5059.5 2287.00  5065.2 2289.66
  5070.2 2289.60  5079.5 2290.97  5119.7 2298.30  5148.5 2304.67  5152.2 2304.67
#Mann=3,-1,0
  4815.2    0.07       0  4977.2    0.07       0  4981.2    0.07       0
Bank Sta=4977.2,4981.2
Exp/Cntr=0.3,0.1

Type RM Length L Ch R = 1,4567,104,104,104
BEGIN DESCRIPTION:
Finn Creek Trib4 8.0
END DESCRIPTION:
XS GIS Cut Line= 3
      1359305.02      6835138.01      1359255.50      6835108.21
      1359133.70      6835108.40
#Sta/Elev= 28
  4942.2 2276.29  4945.1 2276.29  4950.0 2276.28  4955.8 2275.40  4965.5 2275.71
  4971.4 2270.59  4977.2 2267.90  4986.9 2264.32  4990.7 2263.27  4991.0 2262.77
  4994.5 2262.77  4994.7 2263.27  4997.4 2265.16  5000.0 2265.16  5002.7 2265.16
  5010.5 2267.59  5020.5 2269.47  5030.5 2271.17  5040.5 2273.16  5050.5 2273.20
  5060.5 2273.06  5070.5 2273.33  5080.5 2273.70  5090.5 2274.27  5100.5 2275.13
  5110.5 2276.72  5118.7 2277.41  5121.8 2277.41
#Mann=3,-1,0
  4942.2    0.07       0  4990.7    0.07       0  4994.7    0.07       0
Bank Sta=4990.7,4994.7
Exp/Cntr=0.3,0.1

Type RM Length L Ch R = 1,4463,388,388,388
BEGIN DESCRIPTION:
Finn Creek Trib4 4335
END DESCRIPTION:
XS GIS Cut Line= 3
      1359404.46      6835089.28      1359304.90      6835019.81
      1359124.37      6835073.35
#Sta/Elev= 30
  4878.6 2276.65  4886.8 2276.44  4901.6 2275.03  4907.7 2275.16  4922.6 2273.31
  4928.7 2274.01  4937.4 2272.67  4943.5 2272.29  4951.1 2270.19  4964.4 2267.50
  4973.2 2266.16  4979.3 2265.65  4994.1 2262.53  4997.2 2263.32  5002.6 2263.32
  5006.2 2260.22  5006.4 2259.72  5009.9 2259.72  5010.2 2260.22  5020.8 2261.39
  5041.4 2265.68  5046.6 2265.12  5052.0 2266.82  5062.5 2269.35  5079.8 2271.40
  5085.1 2270.60  5113.1 2272.93  5118.3 2271.99  5135.5 2273.76  5188.3 2274.99
#Mann=3,-1,0
  4878.6    0.07       0  5006.2    0.07       0  5010.2    0.07       0
Bank Sta=5006.2,5010.2
Exp/Cntr=0.3,0.1

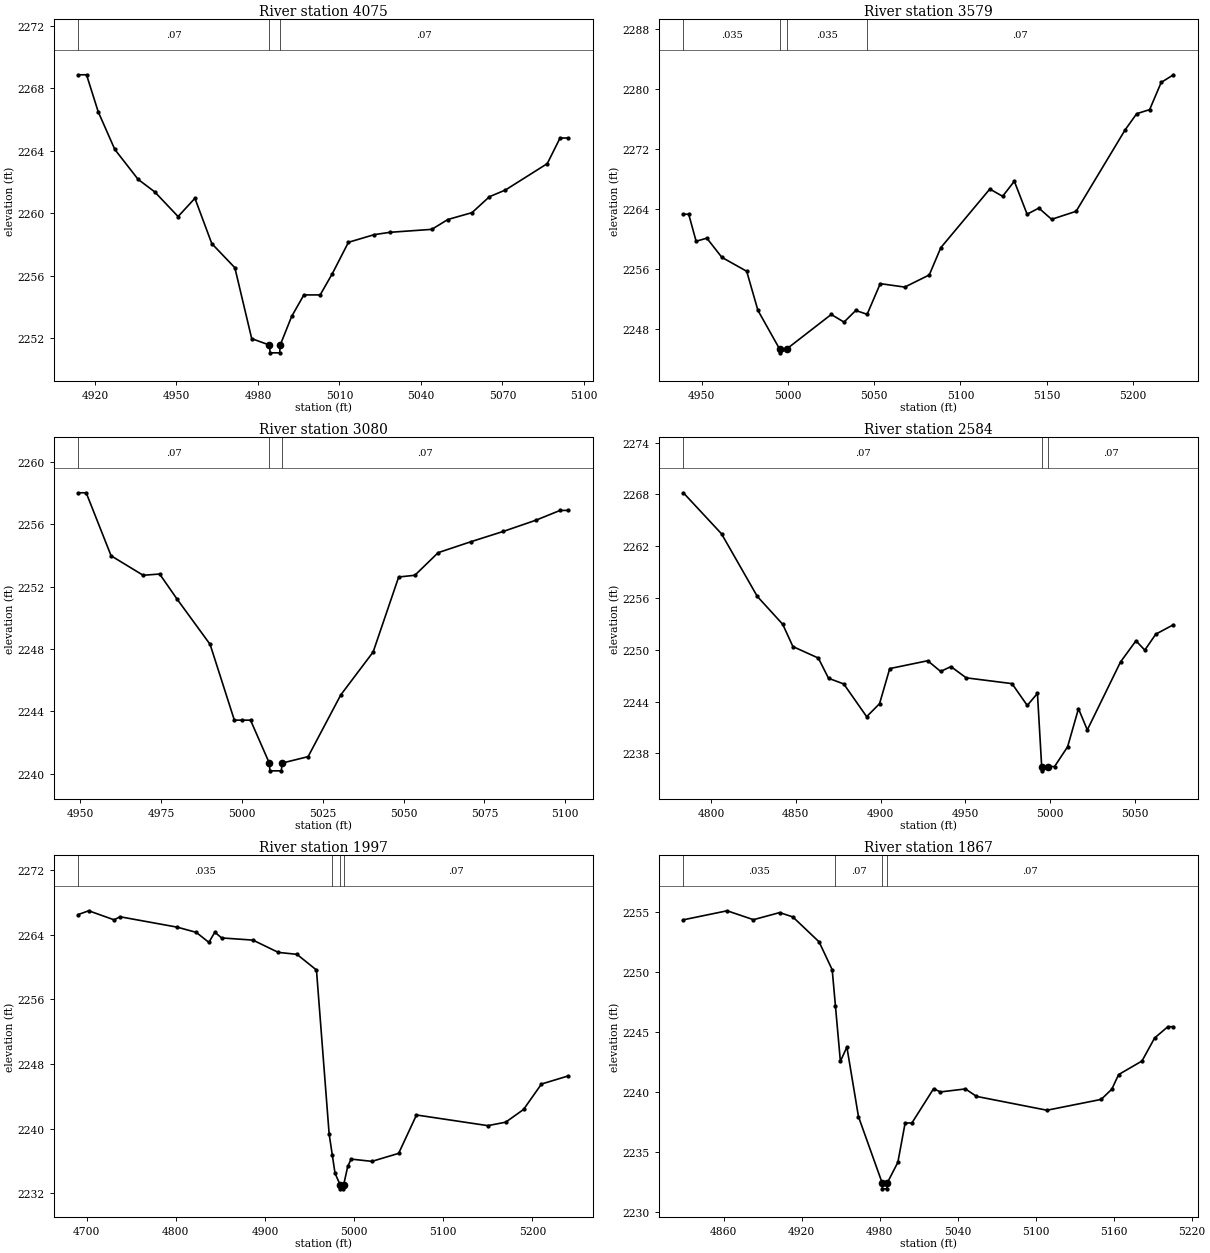
Type RM Length L Ch R = 1,4075,496,496,496
BEGIN DESCRIPTION:
Finn Creek Trib4 7.0
END DESCRIPTION:
XS GIS Cut Line= 3
      1359654.99      6834837.99      1359584.97      6834787.72
      1359504.97      6834737.98
#Sta/Elev= 30
  4913.8 2268.87  4916.9 2268.87  4921.2 2266.50  4927.3 2264.09  4935.9 2262.17
  4942.0 2261.37  4950.6 2259.79  4956.8 2260.96  4963.0 2258.06  4971.5 2256.51
  4977.7 2251.97  4984.2 2251.56  4984.5 2251.06  4988.0 2251.06  4988.2 2251.56
  4992.4 2253.39  4996.9 2254.77  5002.9 2254.77  5007.4 2256.14  5013.3 2258.14
  5022.8 2258.63  5028.6 2258.78  5044.0 2258.97  5049.9 2259.60  5058.8 2260.04
  5065.2 2261.06  5071.1 2261.49  5086.5 2263.18  5091.2 2264.82  5094.2 2264.82
#Mann=3,-1,0
  4913.8    0.07       0  4984.2    0.07       0  4988.2    0.07       0
Bank Sta=4984.2,4988.2
Exp/Cntr=0.3,0.1

Type RM Length L Ch R = 1,3579,499,499,499
BEGIN DESCRIPTION:
Finn Creek Trib4 6.0
END DESCRIPTION:
XS GIS Cut Line= 3
      1359855.02      6834538.03      1359820.18      6834488.45
      1359655.02      6834338.02
#Sta/Elev= 30
  4939.4 2263.36  4942.5 2263.36  4946.8 2259.75  4953.0 2260.17  4961.7 2257.61
  4976.1 2255.75  4982.6 2250.54  4995.2 2245.37  4995.5 2244.87  4999.2 2245.37
  5025.1 2249.99  5032.5 2248.97  5039.3 2250.52  5045.9 2250.01  5053.5 2254.10
  5067.7 2253.64  5081.9 2255.26  5088.6 2258.90  5117.0 2266.72  5124.4 2265.75
  5131.2 2267.76  5138.6 2263.36  5145.4 2264.18  5152.8 2262.68  5167.0 2263.75
  5195.4 2274.61  5202.1 2276.77  5209.6 2277.31  5216.3 2280.94  5223.4 2281.96
#Mann=4,-1,0
  4939.4   0.035       0  4995.2   0.035       0  4999.2   0.035       0
  5045.9    0.07       0
Bank Sta=4995.2,4999.2
Exp/Cntr=0.3,0.1

Type RM Length L Ch R = 1,3080,496,496,496
BEGIN DESCRIPTION:
Finn Creek Trib4 5.0
END DESCRIPTION:
XS GIS Cut Line= 3
      1360255.01      6834387.97      1360265.17      6834338.40
      1360255.00      6834238.01
#Sta/Elev= 25
  4949.4 2258.02  4951.9 2258.02  4959.6 2253.98  4969.5 2252.73  4974.6 2252.81
  4980.0 2251.20  4990.2 2248.30  4997.7 2243.44  5000.0 2243.44  5002.7 2243.44
  5008.5 2240.69  5008.7 2240.19  5012.2 2240.19  5012.5 2240.69  5020.5 2241.10
  5030.6 2245.06  5040.6 2247.81  5048.5 2252.62  5053.5 2252.73  5060.7 2254.18
  5070.8 2254.88  5080.8 2255.54  5090.9 2256.26  5098.4 2256.89  5100.9 2256.89
#Mann=3,-1,0
  4949.4    0.07       0  5008.5    0.07       0  5012.5    0.07       0
Bank Sta=5008.5,5012.5
Exp/Cntr=0.3,0.1

Type RM Length L Ch R = 1,2584,587,587,587
BEGIN DESCRIPTION:
Finn Creek Trib4 4.0
END DESCRIPTION:
XS GIS Cut Line= 3
      1360854.98      6834437.98      1360735.12      6834257.93
      1360755.00      6834188.00
#Sta/Elev= 30
  4783.7 2268.19  4806.2 2263.44  4827.3 2256.19  4842.3 2252.96  4848.3 2250.38
  4863.3 2249.05  4869.3 2246.71  4878.3 2246.05  4891.8 2242.26  4899.4 2243.77
  4905.4 2247.83  4927.8 2248.74  4935.4 2247.50  4941.5 2248.06  4950.5 2246.76
  4977.5 2246.09  4986.5 2243.56  4992.5 2244.96  4995.0 2236.49  4995.2 2235.99
  4999.0 2236.49  5002.6 2236.49  5010.3 2238.78  5016.7 2243.19  5021.9 2240.73
  5041.5 2248.60  5050.6 2251.05  5055.8 2249.97  5062.3 2251.82  5072.7 2252.91
#Mann=3,-1,0
  4783.7    0.07       0  4995.0    0.07       0  4999.0    0.07       0
Bank Sta=4995,4999
Exp/Cntr=0.3,0.1

Type RM Length L Ch R = 1,1997,130,130,130
BEGIN DESCRIPTION:
Finn Creek Trib4 3.0
END DESCRIPTION:
XS GIS Cut Line= 3
      1361447.62      6834432.12      1361244.97      6834198.06
      1361004.98      6834188.00
#Sta/Elev= 30
  4690.4 2266.48  4702.3 2266.95  4730.8 2265.83  4737.4 2266.21  4801.7 2264.92
  4822.9 2264.28  4837.1 2263.04  4843.8 2264.30  4851.4 2263.59  4886.5 2263.32
  4915.0 2261.80  4935.9 2261.56  4957.8 2259.62  4972.0 2239.34  4975.6 2236.69
  4978.6 2234.48  4984.3 2233.04  4984.5 2232.54  4988.0 2232.54  4988.3 2233.04
  4992.9 2235.32  4996.7 2236.22  5020.0 2235.94  5050.0 2236.93  5070.0 2241.68
  5150.1 2240.36  5170.1 2240.79  5190.1 2242.36  5210.2 2245.51  5240.2 2246.51
#Mann=4,-1,0
  4690.4   0.035       0  4975.6    0.07       0  4984.3    0.07       0
  4988.3    0.07       0
Bank Sta=4984.3,4988.3
Exp/Cntr=0.3,0.1

Type RM Length L Ch R = 1,1867,263,263,263
BEGIN DESCRIPTION:
Finn Creek Trib4 2.1
END DESCRIPTION:
XS GIS Cut Line= 3
      1361378.43      6834109.60      1361208.92      6834086.33
      1361011.82      6834145.89
#Sta/Elev= 30
  4828.9 2254.31  4862.6 2255.06  4882.8 2254.32  4903.0 2254.91  4913.1 2254.55
  4933.3 2252.48  4943.4 2250.16  4945.9 2247.14  4949.7 2242.55  4954.7 2243.74
  4963.6 2237.96  4981.8 2232.46  4982.0 2231.96  4985.5 2231.96  4985.8 2232.46
  4993.9 2234.16  4999.5 2237.43  5004.7 2237.43  5021.4 2240.28  5026.6 2240.01
  5045.9 2240.26  5054.4 2239.64  5108.6 2238.49  5150.3 2239.39  5158.5 2240.24
  5163.7 2241.45  5181.7 2242.58  5191.4 2244.49  5201.6 2245.43  5205.9 2245.43
#Mann=4,-1,0
  4828.9   0.035       0  4945.9    0.07       0  4981.8    0.07       0
  4985.8    0.07       0
Bank Sta=4981.8,4985.8
Exp/Cntr=0.3,0.1

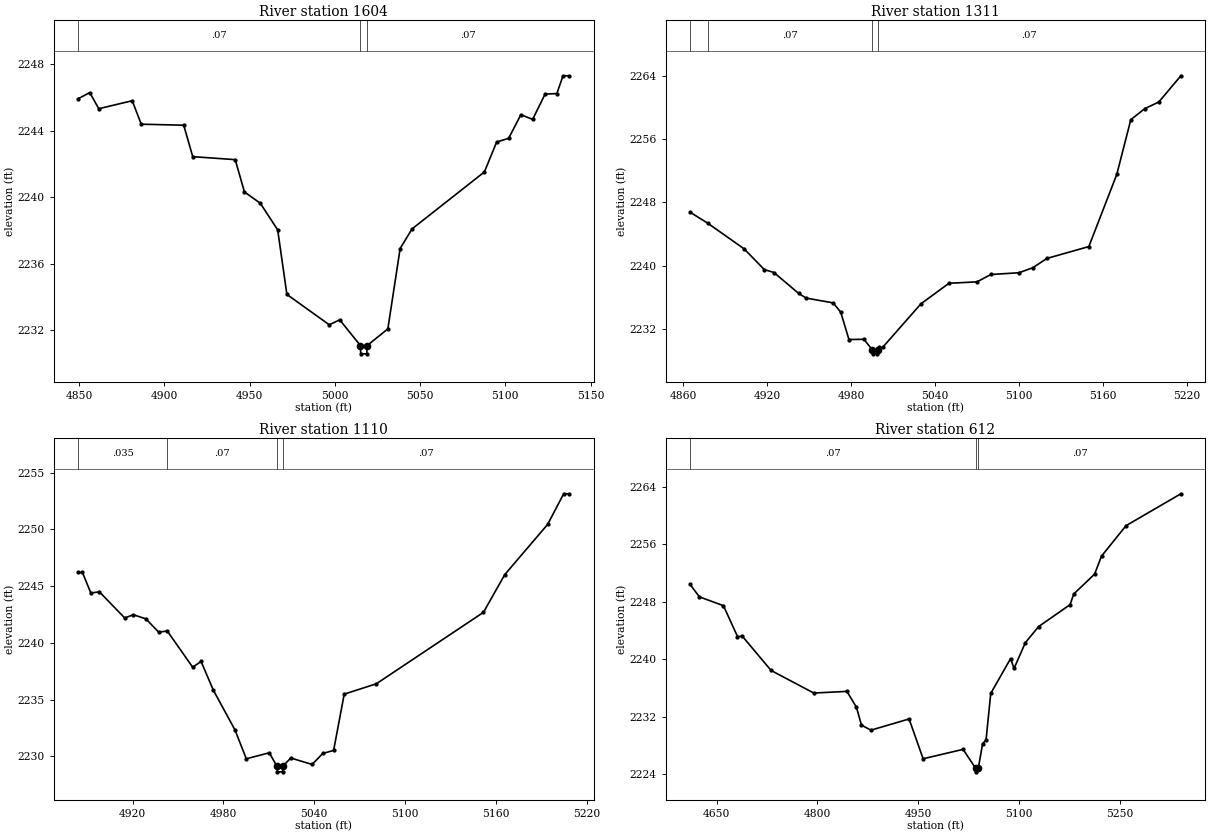
Type RM Length L Ch R = 1,1604,293,293,293
BEGIN DESCRIPTION:
Finn Creek Trib4 2.0
END DESCRIPTION:
XS GIS Cut Line= 3
      1361102.88      6833897.99      1361049.91      6834038.86
      1360954.97      6834138.04
#Sta/Elev= 30
  4849.5 2245.91  4856.3 2246.28  4861.6 2245.31  4881.2 2245.79  4886.5 2244.38
  4911.4 2244.32  4916.7 2242.43  4941.6 2242.25  4947.0 2240.31  4956.3 2239.63
  4966.5 2238.03  4971.9 2234.15  4996.7 2232.33  5002.9 2232.62  5015.0 2231.08
  5015.2 2230.58  5018.7 2230.58  5019.0 2231.08  5031.1 2232.08  5038.3 2236.91
  5045.3 2238.09  5087.7 2241.51  5094.9 2243.31  5101.9 2243.53  5109.1 2244.95
  5116.0 2244.67  5123.3 2246.19  5130.2 2246.22  5133.8 2247.29  5137.3 2247.29
#Mann=3,-1,0
  4849.5    0.07       0  5015.0    0.07       0  5019.0    0.07       0
Bank Sta=5015,5019
Exp/Cntr=0.3,0.1

Type RM Length L Ch R = 1,1311,201,201,201
BEGIN DESCRIPTION:
Finn Creek Trib4 1.1
END DESCRIPTION:
XS GIS Cut Line= 3
      1361131.01      6833871.51      1361004.76      6833822.85
      1360789.21      6833818.21
#Sta/Elev= 30
  4864.7 2246.76  4877.3 2245.37  4903.3 2242.13  4917.8 2239.50  4924.7 2239.13
  4942.4 2236.48  4947.7 2235.90  4967.0 2235.29  4972.4 2234.13  4978.3 2230.66
  4989.0 2230.69  4995.0 2229.35  4995.2 2228.85  4998.7 2228.85  4999.0 2229.35
  4999.8 2229.67  5002.4 2229.67  5029.8 2235.18  5049.8 2237.77  5069.8 2237.95
  5079.8 2238.88  5099.8 2239.10  5109.8 2239.74  5119.8 2240.91  5149.8 2242.41
  5169.8 2251.54  5179.8 2258.45  5189.8 2259.85  5199.8 2260.68  5215.6 2264.00
#Mann=4,-1,0
  4864.7   0.035       0  4877.3    0.07       0  4995.0    0.07       0
  4999.0    0.07       0
Bank Sta=4995,4999
Exp/Cntr=0.3,0.1

Type RM Length L Ch R = 1,1110,498,498,498
BEGIN DESCRIPTION:
Finn Creek Trib4 1.0
END DESCRIPTION:
XS GIS Cut Line= 3
      1361205.01      6833838.03      1361153.40      6833734.14
      1361004.98      6833587.98
#Sta/Elev= 30
  4884.0 2246.21  4886.8 2246.21  4892.4 2244.39  4898.0 2244.50  4914.8 2242.19
  4920.4 2242.48  4928.7 2242.12  4937.2 2240.95  4942.9 2241.04  4959.7 2237.85
  4965.2 2238.36  4973.4 2235.81  4987.6 2232.33  4995.1 2229.78  5010.3 2230.31
  5015.3 2229.13  5015.6 2228.63  5019.1 2228.63  5019.3 2229.13  5024.5 2229.85
  5038.6 2229.28  5045.6 2230.25  5052.8 2230.52  5059.8 2235.48  5081.0 2236.39
  5151.8 2242.69  5165.9 2246.02  5194.2 2250.44  5204.8 2253.14  5208.3 2253.14
#Mann=4,-1,0
  4884.0   0.035       0  4942.9    0.07       0  5015.3    0.07       0
  5019.3    0.07       0
Bank Sta=5015.3,5019.3
Exp/Cntr=0.3,0.1

Type RM Length L Ch R = 1,612,0,0,0
BEGIN DESCRIPTION:
Finn Creek Trib4 0.1
END DESCRIPTION:
XS GIS Cut Line= 3
      1361304.97      6833888.03      1361591.63      6833624.19
      1361510.74      6833293.23
#Sta/Elev= 30
  4610.4 2250.42  4624.3 2248.68  4660.1 2247.45  4681.0 2243.16  4688.4 2243.18
  4731.0 2238.43  4794.5 2235.29  4843.8 2235.52  4858.0 2233.31  4865.4 2230.83
  4879.5 2230.12  4936.3 2231.68  4957.2 2226.14  5016.7 2227.45  5035.3 2224.82
  5035.5 2224.32  5039.3 2224.82  5045.7 2228.24  5050.8 2228.74  5057.8 2235.23
  5087.3 2240.08  5092.5 2238.72  5109.3 2242.30  5129.0 2244.54  5175.8 2247.59
  5181.4 2249.09  5212.3 2251.84  5222.6 2254.35  5259.1 2258.59  5340.7 2263.03
#Mann=3,-1,0
  4610.4    0.07       0  5035.3    0.07       0  5039.3    0.07       0
Bank Sta=5035.3,5039.3
Exp/Cntr=0.3,0.1

Chan Stop Cuts=-1