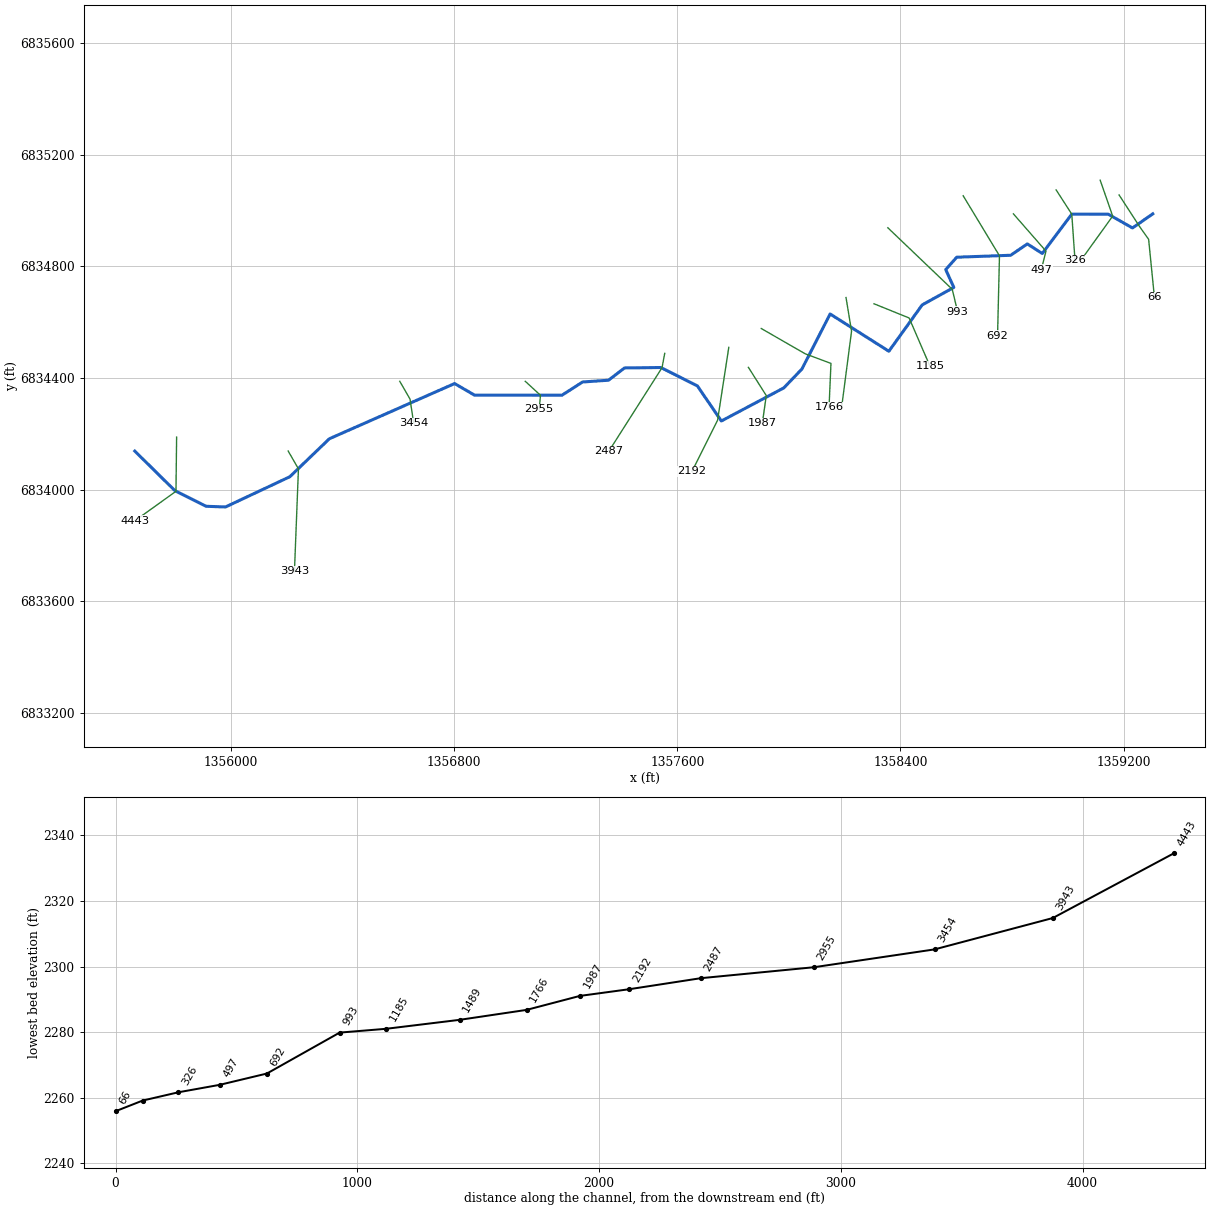
--- Finn Creek Trib4T1.prj (project) ---

Proj Title=Finn Creek Trib4T1 Base Level Engineering
Current Plan=p01
Default Exp/Contr=0.3,0.1
English Units
Geom File=g01
Flow File=f01
Plan File=p01
BEGIN DESCRIPTION:
Finn Creek Trib4T1
END DESCRIPTION:

--- Finn Creek Trib4T1.p01 (plan) ---

Plan Title=Multiple Run
Short Identifier=Multiple
Geom File=g01
Flow File=f01
Subcritical Flow
K Sum by GR= 0
Std Step Tol= 0.01
Critical Tol= 0.01
Num of Std Step Trials= 20
Max Error Tol= 0.3
Flow Tol Ratio= 0.001
Split Flow NTrial= 30
Split Flow Tol= 0.02
Split Flow Ratio= 0.02
Log Output Level= 0
Friction Slope Method= 1
Unsteady Friction Slope Method= 2
Unsteady Bridges Friction Slope Method= 1
Parabolic Critical Depth
Global Vel Dist=  1 , 1 , 1
Global Log Level= 0
CheckData=True
Encroach Param= -1, 0, 0, 0
BEGIN DESCRIPTION:
Multiple Run
END DESCRIPTION:

--- Finn Creek Trib4T1.f01 (steady flow) ---

Flow Title=Multiple
Number of Profiles=7
Profile Names=10-year,25-year,50-year,1pct_min,100-year,1pct_plu,500-year
River Rch & RM= Finn Creek Trib4,Reach-1,4443
     193     271     336     207     413     825     635
Boundary for River Rch & Prof#=Finn Creek Trib4,Reach-1,1
Up Type=0
Dn Type=3
Dn Slope=0.005
Boundary for River Rch & Prof#=Finn Creek Trib4,Reach-1,2
Up Type=0
Dn Type=3
Dn Slope=0.005
Boundary for River Rch & Prof#=Finn Creek Trib4,Reach-1,3
Up Type=0
Dn Type=3
Dn Slope=0.005
Boundary for River Rch & Prof#=Finn Creek Trib4,Reach-1,4
Up Type=0
Dn Type=3
Dn Slope=0.005
Boundary for River Rch & Prof#=Finn Creek Trib4,Reach-1,5
Up Type=0
Dn Type=3
Dn Slope=0.005
Boundary for River Rch & Prof#=Finn Creek Trib4,Reach-1,6
Up Type=0
Dn Type=3
Dn Slope=0.005
Boundary for River Rch & Prof#=Finn Creek Trib4,Reach-1,7
Up Type=0
Dn Type=3
Dn Slope=0.005

--- Finn Creek Trib4T1.g01 (geometry) ---

Geom Title=Existing Conditions

River Reach=Finn Creek Trib4,Reach-1
Reach XY= 30
      1355655.00      6834138.00      1355798.94      6833996.13
      1355910.56      6833940.26      1355980.00      6833937.59
      1356211.06      6834046.14      1356352.70      6834182.17
      1356801.70      6834379.92      1356873.22      6834338.33
      1357186.73      6834338.21      1357260.57      6834385.53
      1357353.40      6834391.86      1357410.94      6834435.75
      1357541.08      6834437.35      1357672.05      6834371.51
      1357758.05      6834245.76      1357981.88      6834364.27
      1358046.87      6834431.93      1358148.05      6834629.16
      1358358.66      6834495.67      1358478.13      6834661.73
      1358591.49      6834724.32      1358562.46      6834788.23
      1358602.00      6834832.54      1358795.41      6834839.54
      1358855.11      6834880.19      1358908.58      6834845.89
      1359014.44      6834986.87      1359145.34      6834986.62
      1359232.15      6834937.39      1359305.00      6834988.00

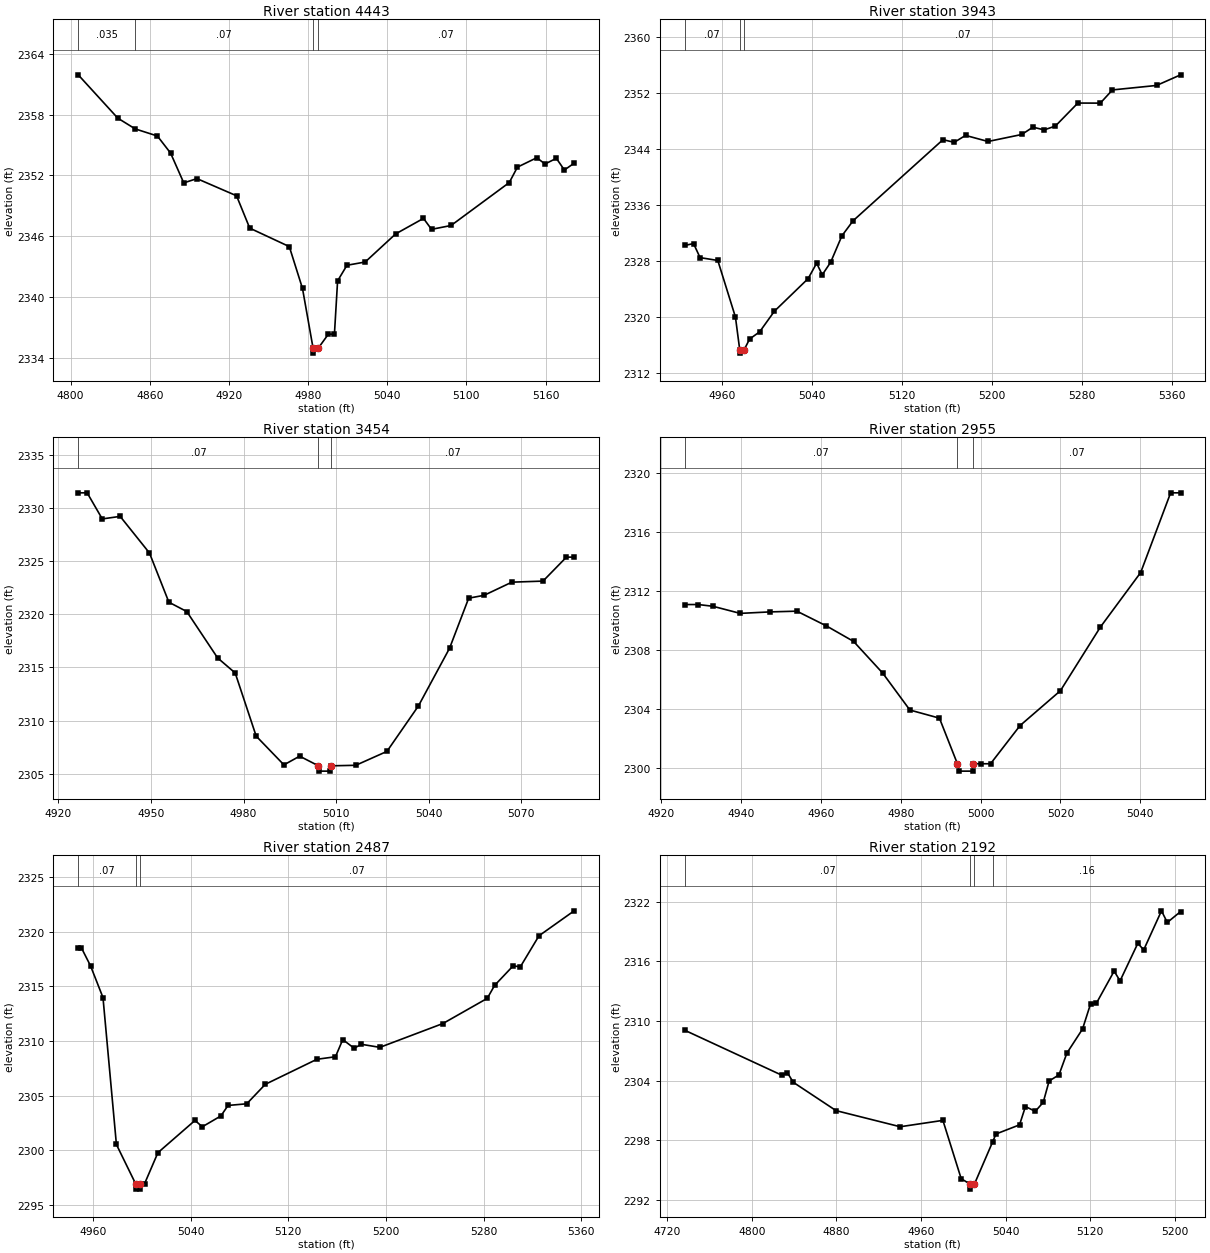
Type RM Length L Ch R = 1,4443,500,500,500
BEGIN DESCRIPTION:
Finn Creek Trib4T1 8.0
END DESCRIPTION:
XS GIS Cut Line= 3
      1355805.00      6834188.01      1355802.70      6833993.83
      1355655.00      6833888.00
#Sta/Elev= 30
  4805.8 2361.92  4835.8 2357.65  4849.0 2356.59  4865.8 2355.89  4875.8 2354.21
  4885.8 2351.27  4895.8 2351.69  4925.8 2350.00  4935.8 2346.81  4965.8 2344.99
  4975.8 2340.86  4983.8 2334.99  4984.1 2334.49  4987.8 2334.99  4995.4 2336.36
  5000.0 2336.36  5002.4 2341.61  5009.5 2343.15  5023.3 2343.47  5046.4 2346.24
  5067.5 2347.77  5073.6 2346.69  5088.4 2347.07  5132.5 2351.30  5138.7 2352.82
  5153.4 2353.75  5159.6 2353.13  5168.2 2353.69  5174.3 2352.54  5181.7 2353.21
#Mann=4,-1,0
  4805.8   0.035       0  4849.0    0.07       0  4983.8    0.07       0
  4987.8    0.07       0
Bank Sta=4983.8,4987.8
Exp/Cntr=0.3,0.1

Type RM Length L Ch R = 1,3943,489,489,489
BEGIN DESCRIPTION:
Finn Creek Trib4T1 7.0
END DESCRIPTION:
XS GIS Cut Line= 3
      1356204.98      6834138.04      1356241.81      6834074.32
      1356227.46      6833706.60
#Sta/Elev= 30
  4926.4 2330.20  4934.3 2330.47  4940.1 2328.46  4955.9 2328.05  4971.6 2319.95
  4975.4 2315.29  4975.7 2314.79  4979.4 2315.29  4984.2 2316.80  4993.2 2317.85
  5006.3 2320.79  5036.3 2325.45  5043.9 2327.66  5048.9 2326.00  5056.4 2327.80
  5066.4 2331.58  5076.4 2333.74  5156.4 2345.34  5166.4 2344.96  5176.5 2345.95
  5196.5 2345.08  5226.5 2346.08  5236.5 2347.13  5246.5 2346.74  5256.5 2347.29
  5276.5 2350.58  5296.5 2350.57  5307.3 2352.46  5346.6 2353.10  5368.0 2354.62
#Mann=3,-1,0
  4926.4    0.07       0  4975.4    0.07       0  4979.4    0.07       0
Bank Sta=4975.4,4979.4
Exp/Cntr=0.3,0.1

Type RM Length L Ch R = 1,3454,499,499,499
BEGIN DESCRIPTION:
Finn Creek Trib4T1 6.0
END DESCRIPTION:
XS GIS Cut Line= 3
      1356605.02      6834387.97      1356641.84      6834324.24
      1356654.99      6834238.04
#Sta/Elev= 26
  4926.4 2331.46  4929.3 2331.46  4934.2 2329.00  4940.0 2329.24  4949.5 2325.79
  4955.8 2321.15  4961.6 2320.27  4971.6 2315.90  4977.3 2314.48  4984.1 2308.53
  4993.1 2305.82  4998.2 2306.64  5004.3 2305.73  5004.6 2305.23  5008.1 2305.23
  5008.3 2305.73  5016.4 2305.78  5026.5 2307.09  5036.7 2311.37  5046.8 2316.81
  5053.0 2321.53  5058.0 2321.80  5067.0 2323.04  5077.1 2323.14  5084.7 2325.40
  5087.2 2325.40
#Mann=3,-1,0
  4926.4    0.07       0  5004.3    0.07       0  5008.3    0.07       0
Bank Sta=5004.3,5008.3
Exp/Cntr=0.3,0.1

Type RM Length L Ch R = 1,2955,468,468,468
BEGIN DESCRIPTION:
Finn Creek Trib4T1 5.0
END DESCRIPTION:
XS GIS Cut Line= 3
      1357054.99      6834388.01      1357109.58      6834337.91
      1357105.00      6834288.02
#Sta/Elev= 23
  4925.9 2311.08  4929.3 2311.08  4933.0 2310.96  4939.8 2310.48  4947.2 2310.58
  4954.0 2310.63  4961.4 2309.63  4968.2 2308.58  4975.5 2306.43  4982.3 2303.93
  4989.7 2303.38  4994.2 2300.29  4994.5 2299.79  4998.0 2299.79  4998.2 2300.29
  5000.0 2300.29  5002.5 2300.29  5009.9 2302.88  5020.0 2305.24  5030.0 2309.55
  5040.1 2313.25  5047.6 2318.65  5050.1 2318.65
#Mann=3,-1,0
  4925.9    0.07       0  4994.2    0.07       0  4998.2    0.07       0
Bank Sta=4994.2,4998.2
Exp/Cntr=0.3,0.1

Type RM Length L Ch R = 1,2487,295,295,295
BEGIN DESCRIPTION:
Finn Creek Trib4T1 4.0
END DESCRIPTION:
XS GIS Cut Line= 3
      1357554.99      6834487.95      1357545.34      6834436.65
      1357354.97      6834137.96
#Sta/Elev= 30
  4947.8 2318.53  4950.3 2318.53  4957.9 2316.86  4968.1 2313.96  4979.1 2300.53
  4994.8 2296.95  4995.0 2296.45  4998.5 2296.45  4998.8 2296.95  5002.2 2296.95
  5013.1 2299.78  5043.5 2302.73  5049.5 2302.15  5064.7 2303.14  5070.6 2304.10
  5085.9 2304.25  5101.1 2306.03  5143.4 2308.32  5158.6 2308.55  5164.6 2310.12
  5173.9 2309.33  5179.8 2309.69  5195.0 2309.41  5246.7 2311.59  5283.0 2313.89
  5289.0 2315.07  5304.2 2316.86  5310.1 2316.77  5325.4 2319.61  5354.2 2321.89
#Mann=3,-1,0
  4947.8    0.07       0  4994.8    0.07       0  4998.8    0.07       0
Bank Sta=4994.8,4998.8
Exp/Cntr=0.3,0.1

Type RM Length L Ch R = 1,2192,205,205,205
BEGIN DESCRIPTION:
Finn Creek Trib4T1 4336
END DESCRIPTION:
XS GIS Cut Line= 3
      1357784.71      6834509.49      1357744.63      6834248.95
      1357652.77      6834065.01
#Sta/Elev= 30
  4736.4 2309.07  4828.5 2304.54  4833.6 2304.80  4839.1 2303.84  4879.6 2300.99
  4940.3 2299.37  4980.7 2300.01  4998.0 2294.15  5006.5 2293.60  5006.8 2293.10
  5010.5 2293.60  5027.8 2297.86  5030.9 2298.64  5053.2 2299.56  5058.8 2301.40
  5068.1 2300.92  5075.6 2301.82  5081.2 2303.97  5090.5 2304.58  5098.0 2306.77
  5112.8 2309.19  5120.4 2311.72  5125.9 2311.78  5142.7 2315.01  5148.3 2314.03
  5165.1 2317.80  5170.7 2317.15  5187.5 2321.07  5193.0 2319.90  5205.6 2321.00
#Mann=4,-1,0
  4736.4    0.07       0  5006.5    0.07       0  5010.5    0.07       0
  5027.8    0.16       0
Bank Sta=5006.5,5010.5
Exp/Cntr=0.3,0.1

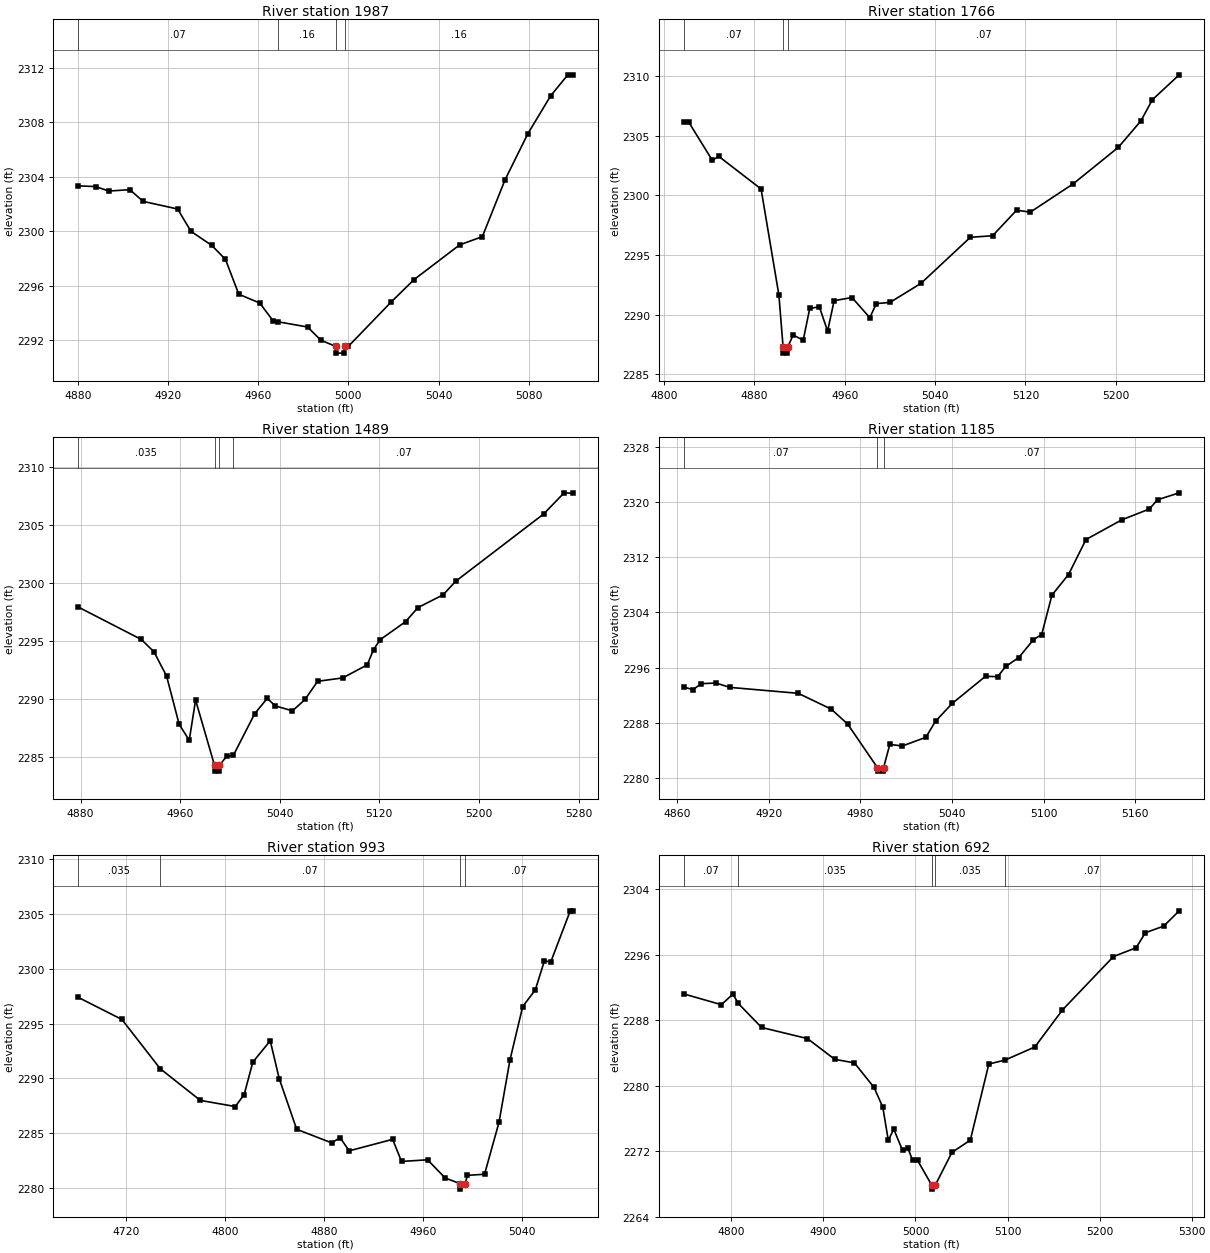
Type RM Length L Ch R = 1,1987,221,221,221
BEGIN DESCRIPTION:
Finn Creek Trib4T1 3.0
END DESCRIPTION:
XS GIS Cut Line= 3
      1357854.99      6834438.02      1357919.12      6834336.83
      1357905.01      6834238.04
#Sta/Elev= 29
  4880.2 2303.34  4887.9 2303.29  4893.8 2302.96  4903.1 2303.06  4909.0 2302.20
  4924.3 2301.64  4930.2 2300.00  4939.4 2298.97  4945.5 2297.94  4951.4 2295.38
  4960.7 2294.73  4966.7 2293.41  4968.6 2293.36  4981.9 2292.97  4987.8 2292.00
  4994.3 2291.55  4994.6 2291.05  4998.1 2291.05  4998.3 2291.55  5000.0 2291.55
  5019.0 2294.81  5029.1 2296.45  5049.3 2299.00  5059.4 2299.61  5069.5 2303.80
  5079.6 2307.18  5089.7 2309.96  5097.3 2311.50  5099.8 2311.50
#Mann=4,-1,0
  4880.2    0.07       0  4968.6    0.16       0  4994.3    0.07       0
  4998.3    0.16       0
Bank Sta=4994.3,4998.3
Exp/Cntr=0.3,0.1

Type RM Length L Ch R = 1,1766,277,277,277
BEGIN DESCRIPTION:
Finn Creek Trib4T1 4337
END DESCRIPTION:
XS GIS Cut Line= 4
      1357901.04      6834577.14      1358059.19      6834486.27
      1358151.03      6834452.15      1358144.08      6834294.17
#Sta/Elev= 30
  4817.6 2306.15  4821.8 2306.15  4842.7 2302.95  4848.5 2303.27  4885.9 2300.54
  4901.7 2291.64  4905.4 2287.28  4905.7 2286.78  4909.2 2286.78  4909.4 2287.28
  4914.4 2288.30  4923.2 2287.86  4929.0 2290.53  4937.5 2290.66  4944.8 2288.63
  4950.6 2291.18  4966.4 2291.44  4982.2 2289.75  4987.9 2290.93  5000.0 2291.03
  5027.5 2292.63  5071.2 2296.49  5090.9 2296.62  5112.1 2298.76  5124.3 2298.60
  5162.2 2300.97  5202.2 2304.03  5222.2 2306.25  5232.3 2308.02  5256.1 2310.11
#Mann=3,-1,0
  4817.6    0.07       0  4905.4    0.07       0  4909.4    0.07       0
Bank Sta=4905.4,4909.4
Exp/Cntr=0.3,0.1

Type RM Length L Ch R = 1,1489,304,304,304
BEGIN DESCRIPTION:
Finn Creek Trib4T1 2.0
END DESCRIPTION:
XS GIS Cut Line= 3
      1358204.99      6834688.05      1358224.84      6834567.77
      1358189.22      6834294.18
#Sta/Elev= 30
  4878.1 2297.91  4928.8 2295.11  4939.0 2294.04  4949.1 2291.95  4959.2 2287.79
  4967.3 2286.41  4972.4 2289.88  4987.6 2284.25  4987.9 2283.75  4991.4 2283.75
  4991.6 2284.25  4997.4 2285.04  5002.7 2285.10  5019.9 2288.71  5030.0 2290.03
  5036.3 2289.38  5050.2 2288.95  5060.3 2289.93  5070.4 2291.50  5090.5 2291.79
  5110.3 2292.92  5115.3 2294.24  5120.8 2295.10  5141.0 2296.64  5151.0 2297.86
  5171.2 2298.96  5181.3 2300.13  5251.9 2305.93  5268.4 2307.76  5275.9 2307.72
#Mann=4,-1,0
  4878.1   0.035       0  4987.6   0.035       0  4991.6   0.035       0
  5002.7    0.07       0
Bank Sta=4987.6,4991.6
Exp/Cntr=0.3,0.1

Type RM Length L Ch R = 1,1185,192,192,192
BEGIN DESCRIPTION:
Finn Creek Trib4T1 4339
END DESCRIPTION:
XS GIS Cut Line= 3
      1358305.55      6834665.69      1358431.27      6834614.87
      1358506.28      6834441.50
#Sta/Elev= 30
  4864.4 2293.18  4870.4 2292.83  4875.8 2293.69  4885.4 2293.78  4894.5 2293.15
  4939.3 2292.29  4960.9 2290.00  4971.7 2287.83  4991.2 2281.52  4991.5 2281.02
  4995.0 2281.02  4995.2 2281.52  4999.3 2284.89  5007.5 2284.66  5022.9 2285.92
  5029.3 2288.26  5040.2 2290.83  5062.0 2294.76  5069.9 2294.70  5075.3 2296.19
  5083.8 2297.47  5093.4 2300.06  5098.8 2300.80  5105.5 2306.51  5116.4 2309.50
  5127.8 2314.56  5151.2 2317.41  5169.3 2318.98  5174.7 2320.32  5188.9 2321.33
#Mann=3,-1,0
  4864.4    0.07       0  4991.2    0.07       0  4995.2    0.07       0
Bank Sta=4991.2,4995.2
Exp/Cntr=0.3,0.1

Type RM Length L Ch R = 1,993,301,301,301
BEGIN DESCRIPTION:
Finn Creek Trib4T1 1.0
END DESCRIPTION:
XS GIS Cut Line= 3
      1358355.01      6834937.99      1358585.79      6834717.62
      1358605.00      6834638.00
#Sta/Elev= 30
  4680.9 2297.39  4716.3 2295.37  4747.3 2290.87  4779.8 2287.97  4808.1 2287.41
  4815.3 2288.51  4822.3 2291.47  4836.4 2293.42  4843.7 2289.95  4857.8 2285.33
  4886.1 2284.09  4893.0 2284.56  4900.3 2283.36  4935.5 2284.41  4942.7 2282.39
  4963.8 2282.54  4978.0 2280.88  4990.1 2280.36  4990.4 2279.86  4994.1 2280.36
  4996.1 2281.12  5009.9 2281.22  5021.6 2285.96  5030.5 2291.67  5040.8 2296.55
  5051.0 2298.07  5058.4 2300.74  5063.5 2300.62  5079.3 2305.30  5081.9 2305.30
#Mann=4,-1,0
  4680.9   0.035       0  4747.3    0.07       0  4990.1    0.07       0
  4994.1    0.07       0
Bank Sta=4990.1,4994.1
Exp/Cntr=0.3,0.1

Type RM Length L Ch R = 1,692,195,195,195
BEGIN DESCRIPTION:
Finn Creek Trib4T1 4338
END DESCRIPTION:
XS GIS Cut Line= 3
      1358625.00      6835052.82      1358755.18      6834837.63
      1358748.29      6834551.21
#Sta/Elev= 30
  4748.5 2291.21  4789.2 2289.90  4801.8 2291.20  4807.4 2290.07  4832.8 2287.12
  4882.7 2285.76  4912.3 2283.23  4933.7 2282.79  4955.0 2279.80  4964.5 2277.40
  4970.5 2273.34  4976.4 2274.71  4986.0 2272.10  4991.9 2272.35  4996.9 2270.89
  5002.3 2270.89  5017.6 2267.88  5017.9 2267.38  5021.6 2267.88  5039.6 2271.86
  5059.6 2273.36  5079.7 2282.65  5097.6 2283.15  5129.7 2284.74  5159.7 2289.26
  5215.1 2295.78  5239.7 2296.85  5249.7 2298.68  5269.7 2299.50  5286.5 2301.36
#Mann=5,-1,0
  4748.5    0.07       0  4807.4   0.035       0  5017.6   0.035       0
  5021.6   0.035       0  5097.6    0.07       0
Bank Sta=5017.6,5021.6
Exp/Cntr=0.3,0.1

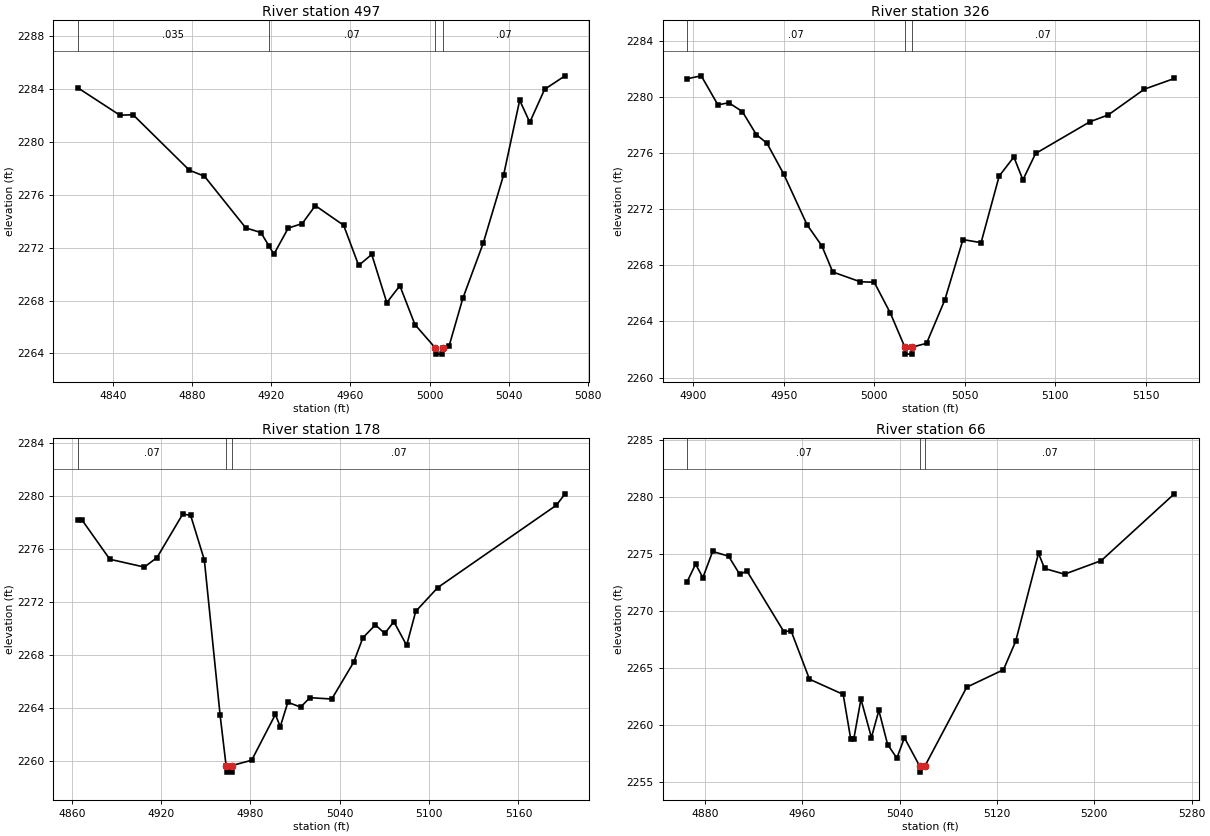
Type RM Length L Ch R = 1,497,171,171,171
BEGIN DESCRIPTION:
Finn Creek Trib4T1 0.1
END DESCRIPTION:
XS GIS Cut Line= 3
      1358805.03      6834987.97      1358922.04      6834854.24
      1358905.00      6834787.99
#Sta/Elev= 30
  4822.3 2284.12  4843.6 2282.04  4850.3 2282.07  4878.7 2277.87  4886.3 2277.42
  4907.2 2273.50  4914.8 2273.15  4919.0 2272.11  4921.4 2271.51  4928.6 2273.48
  4935.7 2273.83  4942.3 2275.19  4956.6 2273.70  4964.2 2270.66  4970.8 2271.49
  4978.4 2267.84  4985.0 2269.12  4992.6 2266.18  5002.7 2264.44  5003.0 2263.94
  5006.5 2263.94  5006.7 2264.44  5009.9 2264.58  5016.8 2268.17  5027.1 2272.35
  5037.4 2277.52  5045.5 2283.17  5050.6 2281.50  5058.1 2284.00  5068.4 2285.02
#Mann=4,-1,0
  4822.3   0.035       0  4919.0    0.07       0  5002.7    0.07       0
  5006.7    0.07       0
Bank Sta=5002.7,5006.7
Exp/Cntr=0.3,0.1

Type RM Length L Ch R = 1,326,148,148,148
BEGIN DESCRIPTION:
Finn Creek Trib4T1 4340
END DESCRIPTION:
XS GIS Cut Line= 3
      1358958.30      6835073.71      1359014.44      6834986.87
      1359025.93      6834821.57
#Sta/Elev= 30
  4896.6 2281.31  4904.5 2281.52  4913.7 2279.45  4919.7 2279.60  4927.2 2278.97
  4934.9 2277.33  4940.8 2276.71  4950.0 2274.52  4962.9 2270.90  4971.1 2269.39
  4977.1 2267.53  4992.3 2266.83  5000.0 2266.80  5008.9 2264.60  5016.9 2262.17
  5017.2 2261.67  5020.7 2261.67  5020.9 2262.17  5028.9 2262.44  5039.0 2265.54
  5049.0 2269.84  5059.0 2269.62  5069.0 2274.37  5077.1 2275.73  5082.1 2274.10
  5089.1 2275.98  5119.2 2278.25  5129.2 2278.73  5149.2 2280.57  5165.7 2281.33
#Mann=3,-1,0
  4896.6    0.07       0  5016.9    0.07       0  5020.9    0.07       0
Bank Sta=5016.9,5020.9
Exp/Cntr=0.3,0.1

Type RM Length L Ch R = 1,178,112,112,112
BEGIN DESCRIPTION:
Finn Creek Trib4T1 4341
END DESCRIPTION:
XS GIS Cut Line= 3
      1359116.32      6835108.37      1359161.08      6834979.84
      1359049.27      6834824.62
#Sta/Elev= 30
  4863.9 2278.23  4866.7 2278.23  4885.5 2275.24  4908.7 2274.65  4917.2 2275.37
  4934.5 2278.66  4939.8 2278.56  4949.0 2275.19  4959.6 2263.44  4963.6 2259.64
  4963.9 2259.14  4967.4 2259.14  4967.6 2259.64  4980.8 2260.04  4996.7 2263.50
  5000.0 2262.58  5005.1 2264.42  5013.7 2264.06  5019.9 2264.77  5034.6 2264.67
  5049.3 2267.45  5055.5 2269.30  5063.9 2270.28  5070.2 2269.63  5076.3 2270.52
  5084.9 2268.73  5091.0 2271.30  5105.8 2273.10  5185.5 2279.33  5191.3 2280.19
#Mann=3,-1,0
  4863.9    0.07       0  4963.6    0.07       0  4967.6    0.07       0
Bank Sta=4963.6,4967.6
Exp/Cntr=0.3,0.1

Type RM Length L Ch R = 1,66,0,0,0
BEGIN DESCRIPTION:
Finn Creek Trib4T1 4342
END DESCRIPTION:
XS GIS Cut Line= 4
      1359183.96      6835055.67      1359257.37      6834942.61
      1359289.92      6834896.60      1359310.75      6834688.29
#Sta/Elev= 30
  4865.2 2272.53  4872.3 2274.11  4878.3 2272.93  4886.3 2275.22  4899.4 2274.81
  4908.6 2273.21  4914.5 2273.51  4944.8 2268.20  4950.8 2268.26  4965.9 2264.03
  4993.6 2262.70  4999.8 2258.79  5002.3 2258.79  5008.2 2262.28  5016.8 2258.92
  5022.9 2261.30  5030.1 2258.31  5037.7 2257.12  5043.9 2258.90  5056.6 2256.39
  5056.8 2255.89  5060.6 2256.39  5095.1 2263.33  5125.3 2264.86  5135.3 2267.34
  5154.1 2275.06  5159.1 2273.73  5175.5 2273.23  5205.7 2274.42  5265.7 2280.27
#Mann=3,-1,0
  4865.2    0.07       0  5056.6    0.07       0  5060.6    0.07       0
Bank Sta=5056.6,5060.6
Exp/Cntr=0.3,0.1

Chan Stop Cuts=-1