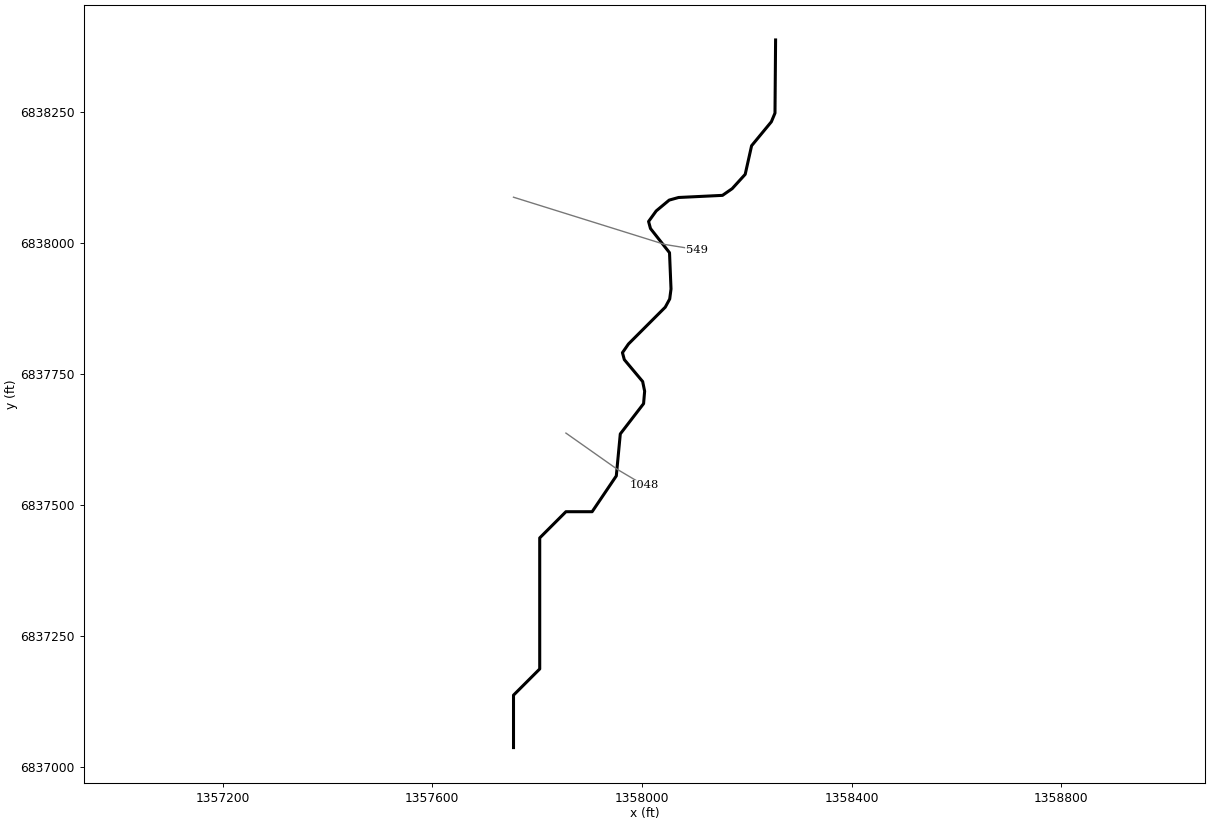
--- Finn Creek Trib5T1.prj (project) ---

Proj Title=Finn Creek Trib5T1 Base Level Engineering
Current Plan=p01
Default Exp/Contr=0.3,0.1
English Units
Geom File=g01
Flow File=f01
Plan File=p01
BEGIN DESCRIPTION:
Finn Creek Trib5T1
END DESCRIPTION:

--- Finn Creek Trib5T1.p01 (plan) ---

Plan Title=Multiple Run
Short Identifier=Multiple
Geom File=g01
Flow File=f01
Subcritical Flow
K Sum by GR= 0
Std Step Tol= 0.01
Critical Tol= 0.01
Num of Std Step Trials= 20
Max Error Tol= 0.3
Flow Tol Ratio= 0.001
Split Flow NTrial= 30
Split Flow Tol= 0.02
Split Flow Ratio= 0.02
Log Output Level= 0
Friction Slope Method= 1
Unsteady Friction Slope Method= 2
Unsteady Bridges Friction Slope Method= 1
Parabolic Critical Depth
Global Vel Dist=  1 , 1 , 1
Global Log Level= 0
CheckData=True
Encroach Param= -1, 0, 0, 0
BEGIN DESCRIPTION:
Multiple Run
END DESCRIPTION:

--- Finn Creek Trib5T1.f01 (steady flow) ---

Flow Title=Multiple
Number of Profiles=7
Profile Names=10-year,25-year,50-year,1pct_min,100-year,1pct_plu,500-year
River Rch & RM= Finn Creek Trib5,Reach-1,1048
     108     147     178     108     215     429     318
Boundary for River Rch & Prof#=Finn Creek Trib5,Reach-1,1
Up Type=0
Dn Type=3
Dn Slope=0.005
Boundary for River Rch & Prof#=Finn Creek Trib5,Reach-1,2
Up Type=0
Dn Type=3
Dn Slope=0.005
Boundary for River Rch & Prof#=Finn Creek Trib5,Reach-1,3
Up Type=0
Dn Type=3
Dn Slope=0.005
Boundary for River Rch & Prof#=Finn Creek Trib5,Reach-1,4
Up Type=0
Dn Type=3
Dn Slope=0.005
Boundary for River Rch & Prof#=Finn Creek Trib5,Reach-1,5
Up Type=0
Dn Type=3
Dn Slope=0.005
Boundary for River Rch & Prof#=Finn Creek Trib5,Reach-1,6
Up Type=0
Dn Type=3
Dn Slope=0.005
Boundary for River Rch & Prof#=Finn Creek Trib5,Reach-1,7
Up Type=0
Dn Type=3
Dn Slope=0.005

--- Finn Creek Trib5T1.g01 (geometry) ---

Geom Title=Existing Conditions

River Reach=Finn Creek Trib5,Reach-1
Reach XY= 30
      1357755.00      6837038.00      1357755.00      6837138.00
      1357805.00      6837188.00      1357805.00      6837438.00
      1357855.00      6837488.00      1357905.00      6837488.00
      1357951.12      6837556.32      1357958.73      6837636.42
      1358003.14      6837694.13      1358005.17      6837717.87
      1358001.38      6837736.37      1357966.39      6837778.13
      1357962.83      6837791.40      1357974.34      6837808.01
      1358044.52      6837878.22      1358053.01      6837893.89
      1358055.48      6837912.97      1358052.63      6837982.12
      1358016.28      6838028.30      1358012.68      6838041.70
      1358027.25      6838061.85      1358052.02      6838082.48
      1358069.95      6838087.47      1358153.71      6838091.53
      1358172.13      6838104.30      1358197.00      6838131.62
      1358209.23      6838186.22      1358246.92      6838231.92
      1358253.85      6838248.47      1358255.00      6838388.00

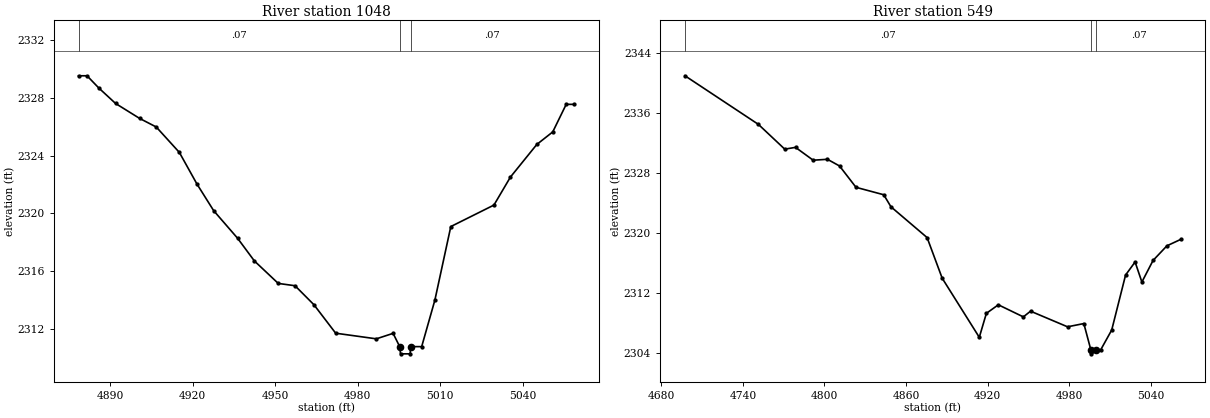
Type RM Length L Ch R = 1,1048,499,499,499
BEGIN DESCRIPTION:
Finn Creek Trib5T1 2.0
END DESCRIPTION:
XS GIS Cut Line= 3
      1357854.99      6837638.01      1357954.38      6837567.95
      1358004.99      6837538.01
#Sta/Elev= 30
  4878.4 2329.53  4881.5 2329.53  4885.8 2328.68  4891.9 2327.61  4900.6 2326.58
  4906.7 2325.98  4915.1 2324.22  4921.5 2322.03  4927.6 2320.18  4936.3 2318.27
  4942.4 2316.70  4951.1 2315.14  4957.2 2314.98  4964.1 2313.66  4972.0 2311.69
  4986.8 2311.30  4992.9 2311.68  4995.3 2310.76  4995.6 2310.26  4999.1 2310.26
  4999.3 2310.76  5003.3 2310.76  5008.1 2313.98  5013.9 2319.08  5029.6 2320.57
  5035.6 2322.51  5045.2 2324.77  5051.0 2325.64  5055.9 2327.55  5058.8 2327.55
#Mann=3,-1,0
  4878.4    0.07       0  4995.3    0.07       0  4999.3    0.07       0
Bank Sta=4995.3,4999.3
Exp/Cntr=0.3,0.1

Type RM Length L Ch R = 1,549,0,0,0
BEGIN DESCRIPTION:
Finn Creek Trib5T1 1.0
END DESCRIPTION:
XS GIS Cut Line= 3
      1357754.96      6838088.01      1358043.80      6837997.81
      1358105.02      6837988.00
#Sta/Elev= 30
  4697.4 2340.93  4751.4 2334.46  4770.8 2331.16  4778.7 2331.40  4791.7 2329.69
  4802.2 2329.81  4811.1 2328.92  4823.2 2326.08  4843.6 2325.09  4848.9 2323.49
  4875.5 2319.39  4886.6 2313.98  4913.9 2306.11  4919.1 2309.30  4927.9 2310.44
  4946.3 2308.83  4951.6 2309.59  4978.8 2307.51  4990.8 2307.94  4996.0 2304.41
  4996.3 2303.91  5000.0 2304.41  5003.1 2304.41  5011.3 2307.08  5021.5 2314.40
  5028.5 2316.14  5033.5 2313.47  5041.7 2316.34  5051.9 2318.29  5062.0 2319.14
#Mann=3,-1,0
  4697.4    0.07       0  4996.0    0.07       0  5000.0    0.07       0
Bank Sta=4996,5000
Exp/Cntr=0.3,0.1

Chan Stop Cuts=-1