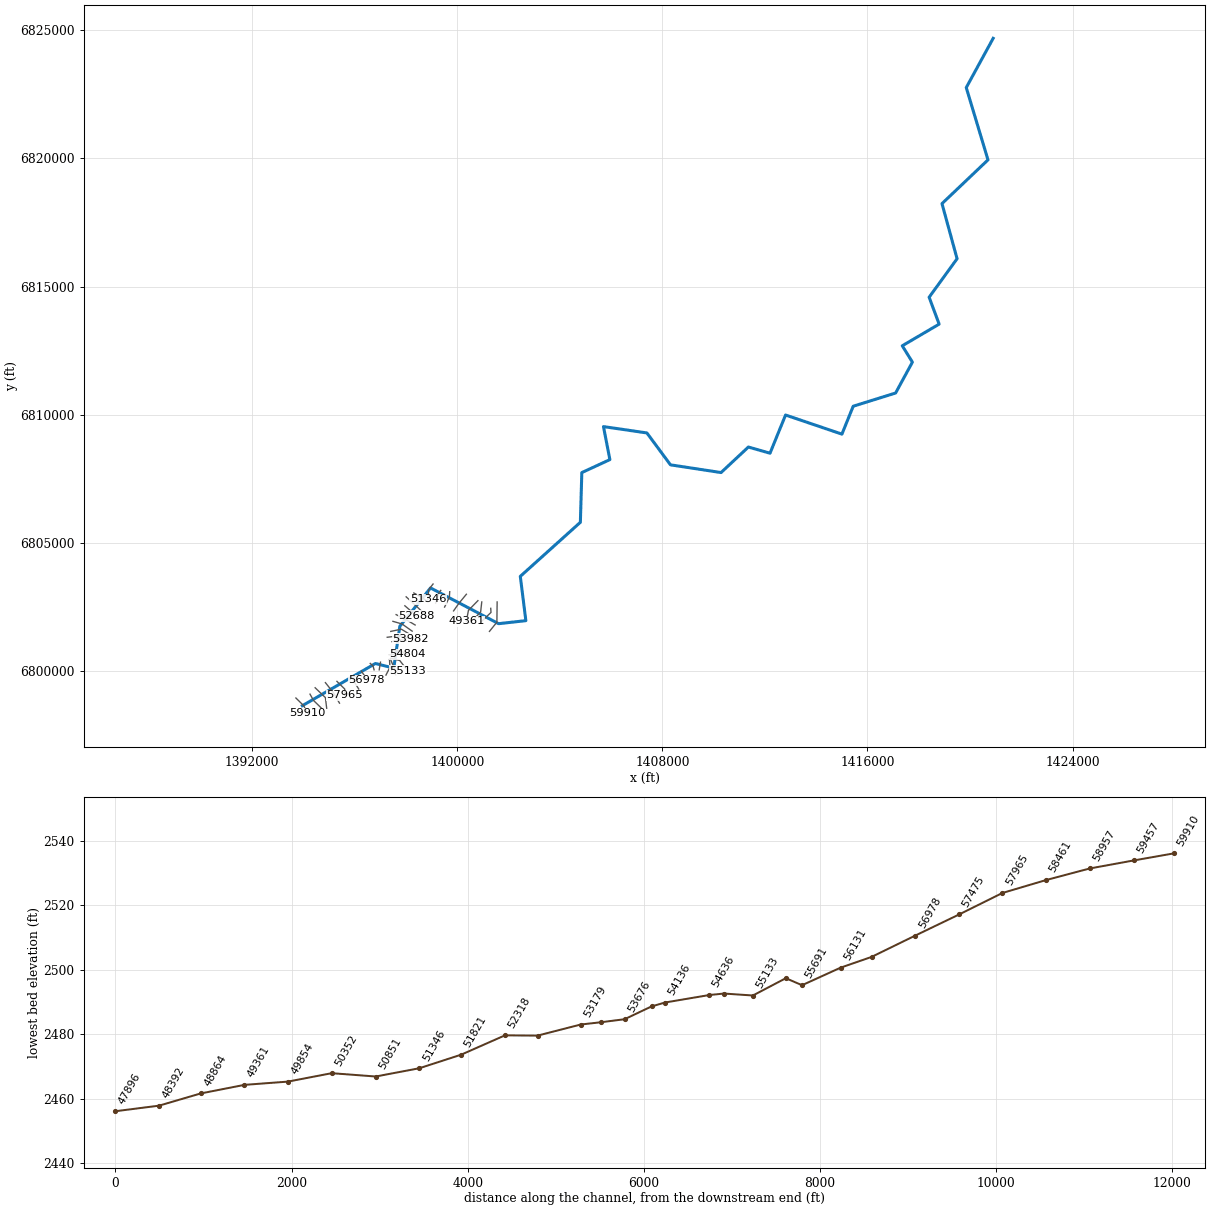
--- Holder Creek.prj (project) ---

Proj Title=Holder Creek Base Level Engineering
Current Plan=p01
Default Exp/Contr=0.3,0.1
English Units
Geom File=g01
Flow File=f01
Plan File=p01
Y Axis Title=Elevation
X Axis Title(PF)=Main Channel Distance
X Axis Title(XS)=Station
BEGIN DESCRIPTION:
Holder Creek
END DESCRIPTION:
DSS Export Rating Curves= 0
DSS Export Rating Curve Sorted= 0
DSS Export Volume Flow Curves= 0
DXF OffsetX= 0
DXF OffsetY= 0
DXF ScaleX= 1
DXF ScaleY= 10

--- Holder Creek.p01 (plan) ---

Plan Title=Multiple Run
Short Identifier=Multiple
Geom File=g01
Flow File=f01
Subcritical Flow
K Sum by GR= 0
Std Step Tol= 0.01
Critical Tol= 0.01
Num of Std Step Trials= 20
Max Error Tol= 0.3
Flow Tol Ratio= 0.001
Split Flow NTrial= 30
Split Flow Tol= 0.02
Split Flow Ratio= 0.02
Log Output Level= 0
Friction Slope Method= 1
Unsteady Friction Slope Method= 2
Unsteady Bridges Friction Slope Method= 1
Parabolic Critical Depth
Global Vel Dist=  1 , 1 , 1
Global Log Level= 0
CheckData=True
Encroach Param= -1, 0, 0, 0
BEGIN DESCRIPTION:
Multiple Run
END DESCRIPTION:

--- Holder Creek.f01 (steady flow) ---

Flow Title=Multiple
Program Version=4.10
Number of Profiles= 7
Profile Names=10-year,25-year,50-year,1pct_min,100-year,1pct_plu,500-year
River Rch & RM=Holder Creek,Reach-1         ,59910
     182     246     297     178     356     710     517
River Rch & RM=Holder Creek,Reach-1         ,58461
     343     483     600     370     738    1472    1131
River Rch & RM=Holder Creek,Reach-1         ,55507
     461     663     833     520    1038    2071    1632
River Rch & RM=Holder Creek,Reach-1         ,51346
     687    1006    1283     811    1619    3229    2610
River Rch & RM=Holder Creek,Reach-1         ,46463
     949    1411    1817    1159    2312    4613    3793
River Rch & RM=Holder Creek,Reach-1         ,39606
     963    1434    1847    1179    2352    4692    3864
River Rch & RM=Holder Creek,Reach-1         ,38112
    1263    1903    2473    1590    3173    6331    5296
River Rch & RM=Holder Creek,Reach-1         ,28973
    1568    2385    3119    2017    4025    8032    6797
River Rch & RM=Holder Creek,Reach-1         ,24243
    1583    2409    3150    2038    4066    8113    6868
River Rch & RM=Holder Creek,Reach-1         ,22280
    1820    2783    3653    2372    4732    9442    8047
River Rch & RM=Holder Creek,Reach-1         ,16580
    1898    2909    3823    2485    4958    9892    8450
River Rch & RM=Holder Creek,Reach-1         ,12496
    1957    3002    3948    2568    5123   10222    8745
River Rch & RM=Holder Creek,Reach-1         ,8918
    2029    3116    4102    2670    5327   10629    9106
River Rch & RM=Holder Creek,Reach-1         ,8390
    2067    3173    4177    2718    5423   10821    9267
Boundary for River Rch & Prof#=Holder Creek,Reach-1         , 1
Up Type= 0
Dn Type= 3
Dn Slope=0.006
Boundary for River Rch & Prof#=Holder Creek,Reach-1         , 2
Up Type= 0
Dn Type= 3
Dn Slope=0.006
Boundary for River Rch & Prof#=Holder Creek,Reach-1         , 3
Up Type= 0
Dn Type= 3
Dn Slope=0.006
Boundary for River Rch & Prof#=Holder Creek,Reach-1         , 4
Up Type= 0
Dn Type= 3
Dn Slope=0.006
Boundary for River Rch & Prof#=Holder Creek,Reach-1         , 5
Up Type= 0
Dn Type= 3
Dn Slope=0.006
Boundary for River Rch & Prof#=Holder Creek,Reach-1         , 6
Up Type= 0
Dn Type= 3
Dn Slope=0.006
Boundary for River Rch & Prof#=Holder Creek,Reach-1         , 7
Up Type= 0
Dn Type= 3
Dn Slope=0.006
DSS Import GetInterval= 0
DSS Import GetPeak= 0
DSS Import FillOption= 0

--- Holder Creek.g01 (geometry) ---

Geom Title=Existing Conditions
Program Version=4.10

River Reach=Holder Creek    ,Reach-1
Reach XY= 30
        1393955.        6798638.      1396806.65       6800284.9
      1397521.68      6800104.22      1397758.11      6801736.35
       1398956.5      6803234.54      1401611.05      6801839.58
      1402675.57      6801957.58      1402458.75      6803686.45
       1404801.5      6805796.46      1404858.04      6807736.58
      1405953.04      6808243.88      1405702.55      6809532.54
      1407396.52      6809284.49      1408316.85       6808039.5
      1410289.77      6807738.24      1411356.64      6808734.86
      1412199.91      6808493.44      1412806.57      6809984.57
        1415005.        6809238.       1415445.3      6810327.23
      1417099.89      6810843.47      1417754.02      6812048.28
      1417358.54      6812686.56      1418797.32      6813531.56
      1418407.06      6814582.14      1419496.92       6816084.7
      1418908.45      6818236.51      1420703.03      6819943.89
      1419854.91      6822765.31        1420905.        6824688.

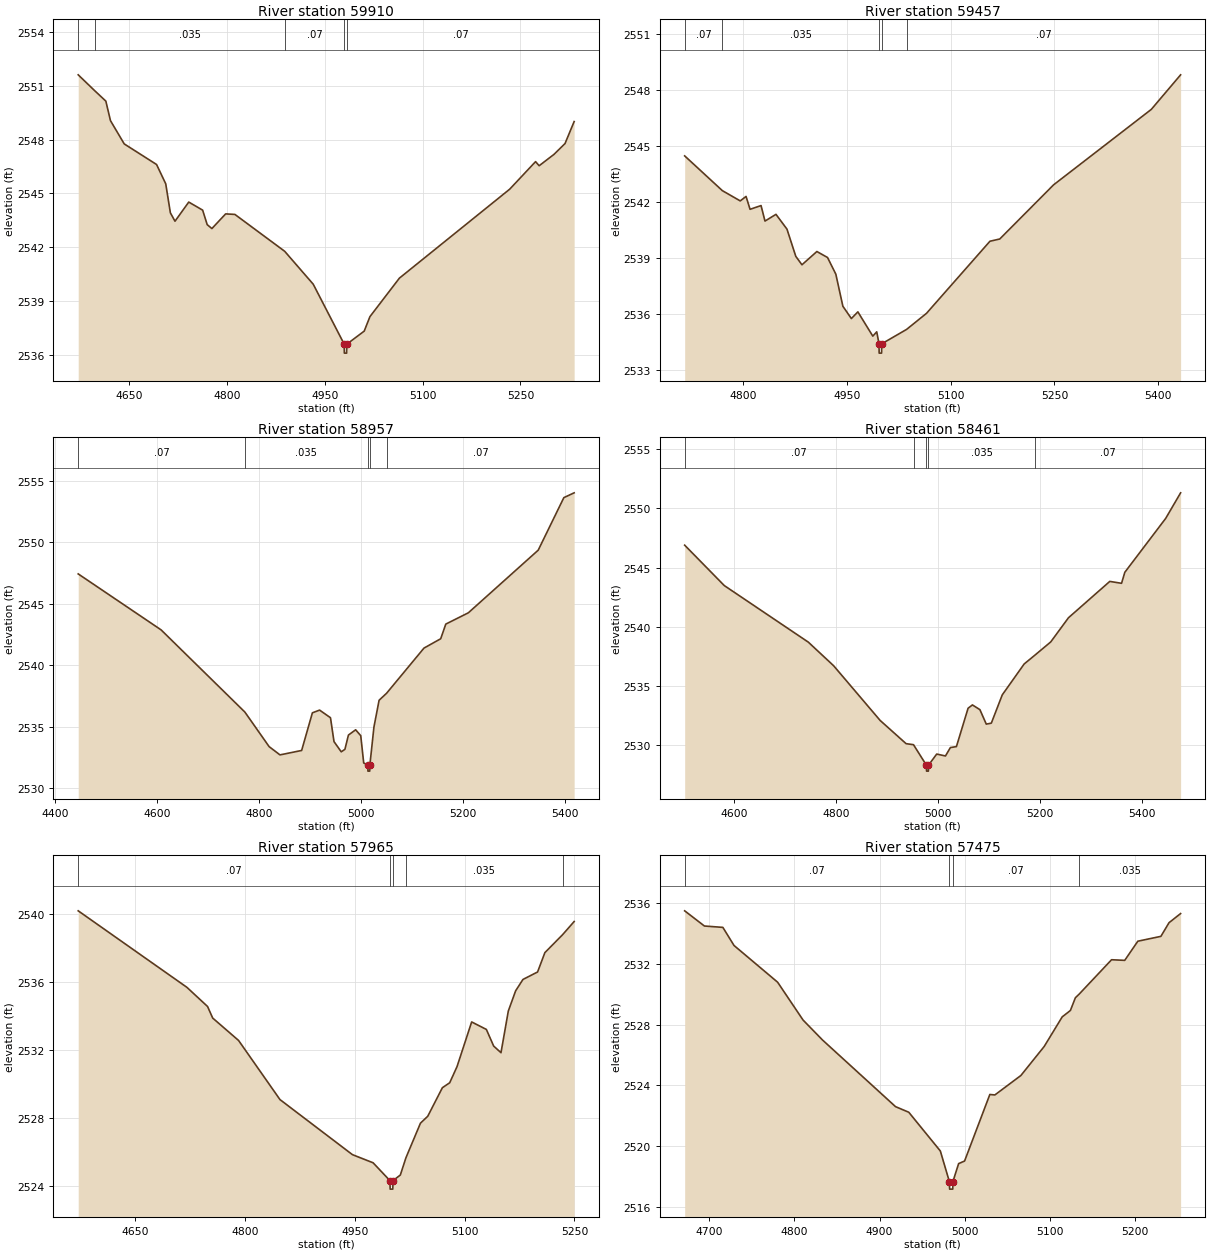
Type RM Length L Ch R = 1 ,59910   ,453,453,453
BEGIN DESCRIPTION:
Holder Creek 106.0
END DESCRIPTION:
XS GIS Cut Line= 3
      1393705.01      6798937.99      1394010.29       6798637.3
      1394154.98      6798338.04
#Sta/Elev= 30
  4571.5 2551.63  4596.9 2550.74  4613.9 2550.16    4621 2549.07  4642.1 2547.77
  4691.7 2546.62  4705.8 2545.54  4712.9 2543.92    4720 2543.45  4741.1 2544.52
  4762.4 2544.07  4769.4 2543.26  4776.6 2543.04  4797.7 2543.86  4811.9 2543.83
  4888.3 2541.77  4932.1 2539.93  4979.6 2536.58  4979.8 2536.08  4983.3 2536.08
  4983.6 2536.58  5010.3 2537.31  5019.1 2538.12  5064.3 2540.27  5233.5 2545.24
  5273.2 2546.78  5278.7 2546.55  5301.3 2547.18  5318.4 2547.79  5332.4 2549.02
#Mann= 5 ,-1 , 0
  4571.5     .07       0  4596.9    .035       0  4888.3     .07       0
  4979.6     .07       0  4983.6     .07       0
Bank Sta=4979.6,4983.6
XS Rating Curve= 0 ,0
Exp/Cntr=0.3,0.1

Type RM Length L Ch R = 1 ,59457   ,500,500,500
BEGIN DESCRIPTION:
Holder Creek 105.0
END DESCRIPTION:
XS GIS Cut Line= 3
        1394255.      6799087.99      1394395.15      6798839.83
      1394705.03      6798537.97
#Sta/Elev= 30
    4715 2544.46  4769.5  2542.6  4795.4 2542.05  4803.8 2542.29  4809.6  2541.6
  4825.5  2541.8  4831.2 2540.97  4847.1 2541.33    4863 2540.54  4875.8 2539.08
  4884.7 2538.63  4906.3 2539.34  4921.7 2539.02  4933.7 2538.13  4943.9 2536.41
  4956.2 2535.75  4965.6 2536.11  4987.2 2534.81  4992.9 2535.04  4996.2  2534.4
  4996.4  2533.9  4999.9  2533.9  5000.2  2534.4  5036.1 2535.17  5064.9 2536.03
  5156.7 2539.89  5170.9 2540.01  5248.8 2542.91  5390.2 2546.95  5432.6  2548.8
#Mann= 5 ,-1 , 0
    4715     .07       0  4769.5    .035       0  4996.2    .035       0
  5000.2    .035       0  5036.1     .07       0
Bank Sta=4996.2,5000.2
XS Rating Curve= 0 ,0
Exp/Cntr=0.3,0.1

Type RM Length L Ch R = 1 ,58957   ,496,496,496
BEGIN DESCRIPTION:
Holder Creek 104.0
END DESCRIPTION:
XS GIS Cut Line= 3
      1394455.03      6799337.97      1394854.83      6798953.74
        1394905.      6798537.96
#Sta/Elev= 30
  4445.5 2547.44  4608.2 2542.89  4772.6 2536.21  4820.2  2533.4  4841.5 2532.73
    4884 2533.09  4905.1 2536.15  4919.2 2536.37  4940.6 2535.75  4947.5 2533.81
  4961.7 2532.98  4968.9 2533.18  4975.8 2534.34    4990 2534.77    5000 2534.29
  5005.8 2532.07  5013.9 2531.91  5014.1 2531.41  5017.6 2531.41  5017.9 2531.91
  5025.9    2535    5036 2537.17  5050.7 2537.74  5124.1 2541.41  5156.9 2542.17
  5166.9 2543.36  5211.2 2544.28  5348.3 2549.37  5398.6 2553.64  5418.8 2554.03
#Mann= 5 ,-1 , 0
  4445.5     .07       0  4772.6    .035       0  5013.9    .035       0
  5017.9    .035       0  5050.7     .07       0
Bank Sta=5013.9,5017.9
XS Rating Curve= 0 ,0
Exp/Cntr=0.3,0.1

Type RM Length L Ch R = 1 ,58461   ,496,496,496
BEGIN DESCRIPTION:
Holder Creek 103.0
END DESCRIPTION:
XS GIS Cut Line= 3
      1394855.01      6799537.99      1395164.65      6799148.85
      1395405.01      6798737.99
#Sta/Elev= 30
  4502.7  2546.9  4580.4 2543.49  4745.4 2538.71    4795 2536.72  4886.3  2532.1
  4937.2 2530.14  4951.8 2530.05  4977.1 2528.32  4977.4 2527.82    4981 2527.82
  4981.2 2528.32  4997.3 2529.26  5014.5  2529.1  5024.2 2529.81    5036 2529.89
  5058.9 2533.13  5067.4 2533.41  5082.1 2533.01  5094.6 2531.79  5104.5 2531.87
    5126 2534.26    5169 2536.87  5190.8 2537.64  5221.1 2538.73  5255.9 2540.77
    5337 2543.84  5360.1 2543.68  5366.5 2544.61  5446.7 2549.16    5476 2551.32
#Mann= 5 ,-1 , 0
  4502.7     .07       0  4951.8    .035       0  4977.1    .035       0
  4981.2    .035       0  5190.8     .07       0
Bank Sta=4977.1,4981.2
XS Rating Curve= 0 ,0
Exp/Cntr=0.3,0.1

Type RM Length L Ch R = 1 ,57965   ,490,490,490
BEGIN DESCRIPTION:
Holder Creek 102.0
END DESCRIPTION:
XS GIS Cut Line= 3
      1395304.99      6799588.01       1395610.2      6799287.52
        1395605.      6799037.98
#Sta/Elev= 30
  4571.7 2540.19  4720.2 2535.69  4748.5 2534.56  4755.5 2533.88  4790.9 2532.56
  4847.5 2529.08  4946.5 2525.84  4974.8 2525.36  4997.8 2524.31  4998.1 2523.81
  5001.7 2523.81    5002 2524.31    5012 2524.64  5019.7 2525.66  5039.5 2527.69
  5049.5  2528.1  5069.5 2529.78  5079.5 2530.07  5089.5 2531.02  5109.5 2533.65
  5129.6 2533.21  5139.6 2532.23  5149.6 2531.84  5159.6 2534.29  5169.6 2535.48
  5179.6 2536.15  5199.6 2536.59  5209.6 2537.73  5233.9 2538.79  5249.6 2539.56
#Mann= 5 ,-1 , 0
  4571.7     .07       0  4997.8     .07       0    5002     .07       0
  5019.7    .035       0  5233.9     .07       0
Bank Sta=4997.8,5002
XS Rating Curve= 0 ,0
Exp/Cntr=0.3,0.1

Type RM Length L Ch R = 1 ,57475   ,497,497,497
BEGIN DESCRIPTION:
Holder Creek 101.0
END DESCRIPTION:
XS GIS Cut Line= 3
      1395855.02      6799787.97      1396022.08      6799504.42
      1396155.01      6799287.98
#Sta/Elev= 30
  4670.9 2535.49  4694.1 2534.49  4715.8  2534.4  4728.9 2533.21  4780.2 2530.79
  4810.1  2528.3  4832.9 2526.99  4918.8  2522.6  4934.4 2522.23  4971.5 2519.68
  4982.1 2517.67  4982.4 2517.17  4986.1 2517.17  4986.3 2517.67    4993 2518.85
    5000 2519.02  5029.7  2523.4  5035.6 2523.37  5066.2 2524.65  5093.6 2526.56
  5114.8 2528.51  5124.4 2528.93  5130.3 2529.77  5134.6    2530  5172.8 2532.27
  5188.3 2532.23  5203.7 2533.49  5230.8 2533.81  5240.4 2534.71    5254 2535.31
#Mann= 4 ,-1 , 0
  4670.9     .07       0  4982.1     .07       0  4986.3     .07       0
  5134.6    .035       0
Bank Sta=4982.1,4986.3
XS Rating Curve= 0 ,0
Exp/Cntr=0.3,0.1

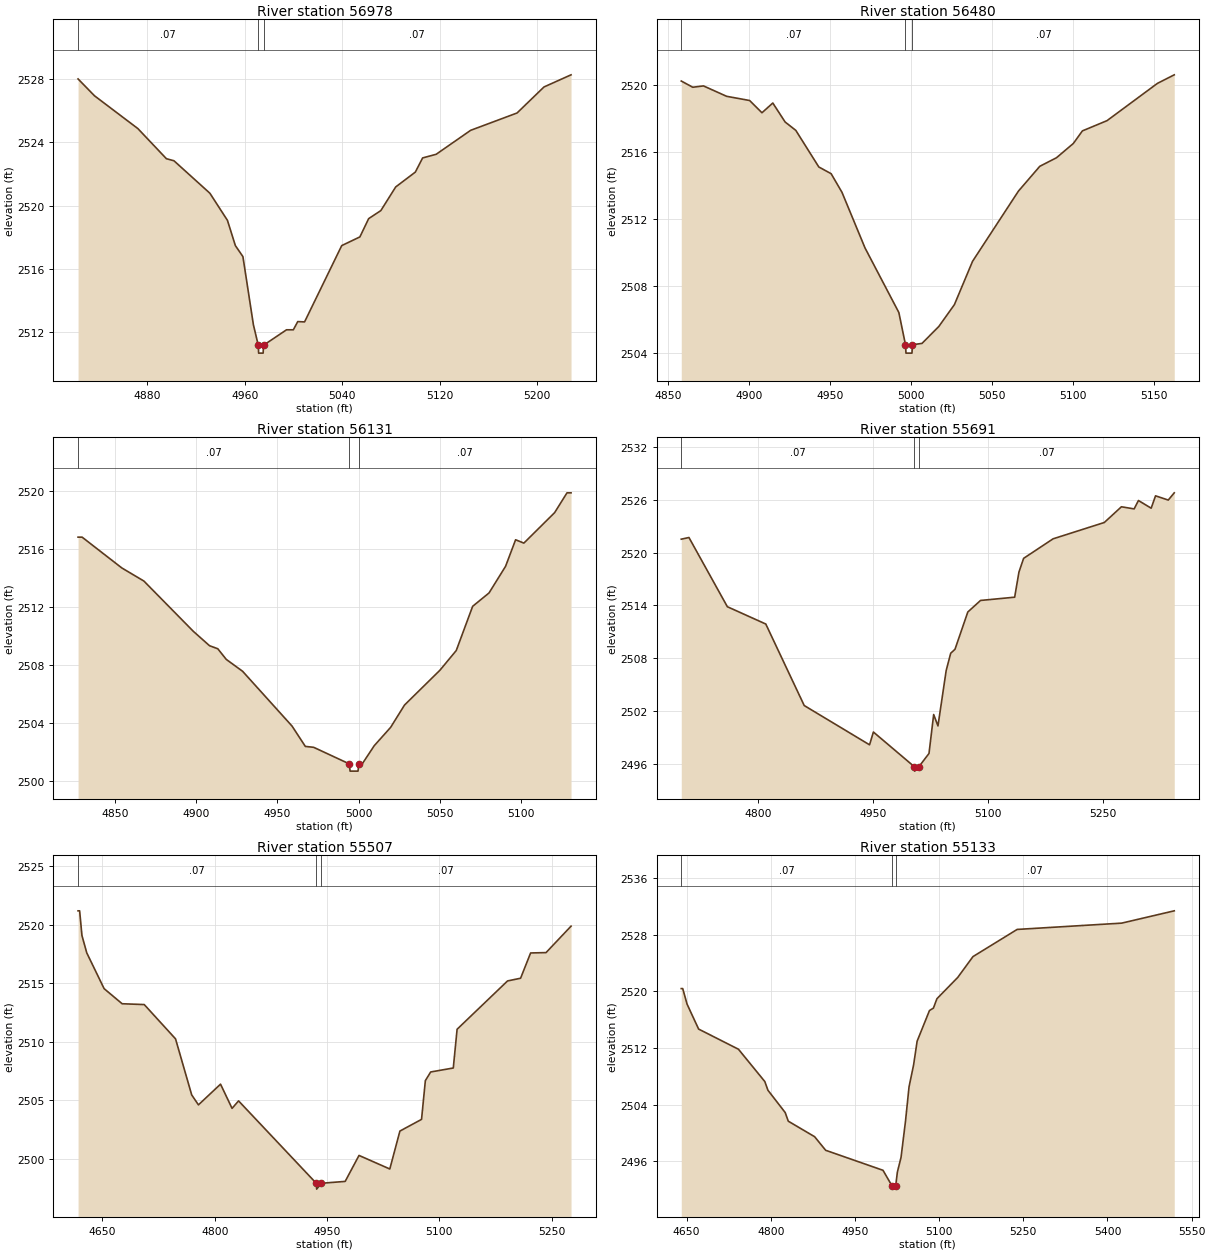
Type RM Length L Ch R = 1 ,56978   ,498,498,498
BEGIN DESCRIPTION:
Holder Creek 100.0
END DESCRIPTION:
XS GIS Cut Line= 3
      1396255.03      6799987.96      1396357.29      6799843.86
      1396455.01      6799637.97
#Sta/Elev= 30
  4823.3 2528.03  4836.8 2526.96  4872.4 2524.88  4895.8 2522.97    4902 2522.84
  4931.5 2520.78  4945.9 2519.06  4952.4 2517.46  4958.6 2516.76  4967.2 2512.44
  4971.2 2511.14  4971.5 2510.64  4975.2 2510.64  4975.5 2511.14  4994.4 2512.12
    5000 2512.12  5003.6 2512.64  5009.2 2512.62  5039.7 2517.46  5054.6 2518.01
  5061.8 2519.17  5071.8 2519.68    5084 2521.18  5100.1 2522.12  5106.1 2523.02
  5117.2 2523.25  5145.5 2524.77  5183.6 2525.87  5205.7 2527.52  5227.9 2528.29
#Mann= 3 ,-1 , 0
  4823.3     .07       0  4971.2     .07       0  4975.5     .07       0
Bank Sta=4971.2,4975.5
XS Rating Curve= 0 ,0
Exp/Cntr=0.3,0.1

Type RM Length L Ch R = 1 ,56480   ,349,349,349
BEGIN DESCRIPTION:
Holder Creek 99.0
END DESCRIPTION:
XS GIS Cut Line= 3
      1396605.01      6800287.99      1396711.66      6800194.69
      1396755.01      6800037.97
#Sta/Elev= 30
  4858.3 2520.21  4865.4 2519.84    4872 2519.92  4886.3  2519.3  4900.5 2519.05
  4908.1 2518.32  4914.8  2518.9  4922.4 2517.77    4929 2517.27  4943.2 2515.09
  4950.8 2514.69  4957.5 2513.58  4971.7 2510.27  4992.6 2506.42  4996.7  2504.5
    4997    2504  5000.7    2504    5001  2504.5  5006.9 2504.58  5017.3 2505.59
  5026.9 2506.89  5038.1 2509.47  5066.4 2513.65  5079.6 2515.13  5089.9 2515.64
  5100.3 2516.49  5105.9 2517.24  5121.1 2517.85  5152.2 2520.07  5162.6 2520.58
#Mann= 3 ,-1 , 0
  4858.3     .07       0  4996.7     .07       0    5001     .07       0
Bank Sta=4996.7,5001
XS Rating Curve= 0 ,0
Exp/Cntr=0.3,0.1

Type RM Length L Ch R = 1 ,56131   ,440,440,440
BEGIN DESCRIPTION:
Holder Creek 98.0
END DESCRIPTION:
XS GIS Cut Line= 3
      1397004.99      6800337.97      1396974.84      6800167.61
        1396955.      6800038.02
#Sta/Elev= 30
    4827  2516.8  4829.5  2516.8    4854 2514.68  4867.6 2513.78  4898.1 2510.32
  4908.1 2509.33  4913.2 2509.12  4918.4 2508.39  4928.5 2507.57    4959  2503.8
  4967.2  2502.4  4972.3 2502.34  4994.3  2501.2  4994.8  2500.7  4999.7  2500.7
  5000.2  2501.2  5002.3  2501.2  5009.7 2502.45  5019.8 2503.71  5028.4 2505.25
  5050.2 2507.64  5060.3    2509  5070.4 2512.04  5080.5 2512.96  5090.7 2514.79
  5096.9 2516.62    5102 2516.39    5121 2518.49  5128.6 2519.85  5131.1 2519.85
#Mann= 3 ,-1 , 0
    4827     .07       0  4994.3     .07       0  5000.2     .07       0
Bank Sta=4994.3,5000.2
XS Rating Curve= 0 ,0
Exp/Cntr=0.3,0.1

Type RM Length L Ch R = 1 ,55691   ,184,184,184
BEGIN DESCRIPTION:
Holder Creek 97.0
END DESCRIPTION:
XS GIS Cut Line= 3
        1397355.      6800437.96      1397373.33      6800138.42
      1397218.06      6799832.91
#Sta/Elev= 30
  4699.9 2521.51  4709.9  2521.7    4760 2513.86  4810.1  2511.9  4860.2 2502.67
  4945.4 2498.22  4950.4 2499.67  5003.8 2495.74  5004.2 2495.24  5009.7 2495.74
  5022.9 2497.24    5029 2501.65  5034.6 2500.36  5045.3 2506.63  5051.2 2508.59
  5056.8 2509.04  5073.5 2513.26  5090.1 2514.57  5134.6 2514.94  5140.2 2517.79
  5146.3 2519.34  5184.7 2521.55  5251.5  2523.4  5273.8 2525.18  5290.4 2524.94
    5296 2525.89  5312.6 2525.02  5318.3 2526.42  5334.9 2525.94  5342.7 2526.76
#Mann= 3 ,-1 , 0
  4699.9     .07       0  5003.8     .07       0  5009.7     .07       0
Bank Sta=5003.8,5009.7
XS Rating Curve= 0 ,0
Exp/Cntr=0.3,0.1

Type RM Length L Ch R = 1 ,55507   ,374,374,374
BEGIN DESCRIPTION:
Holder Creek 4435
END DESCRIPTION:
XS GIS Cut Line= 3
      1397388.39      6800468.74      1397531.82      6800114.04
      1397594.99      6799845.47
#Sta/Elev= 30
  4617.4 2521.19  4619.5 2521.19  4622.6 2519.08    4629  2517.6  4652.2 2514.54
  4676.3 2513.25  4705.8 2513.18  4747.6 2510.25  4769.2 2505.46  4778.2 2504.61
  4807.7 2506.38  4823.1 2504.31  4831.8 2504.95  4935.6 2497.91  4936.1 2497.41
  4942.5 2497.91  4974.2 2498.07  4992.7 2500.29  5033.8 2499.13  5047.3 2502.37
  5076.2 2503.37  5081.3 2506.68  5088.4 2507.42  5118.6 2507.76  5123.7 2511.07
  5191.1  2515.2  5208.5 2515.43  5221.9 2517.59  5242.5 2517.62  5275.9 2519.88
#Mann= 3 ,-1 , 0
  4617.4     .07       0  4935.6     .07       0  4942.5     .07       0
Bank Sta=4935.6,4942.5
XS Rating Curve= 0 ,0
Exp/Cntr=0.3,0.1

Type RM Length L Ch R = 1 ,55133   ,329,329,329
BEGIN DESCRIPTION:
Holder Creek 96.0
END DESCRIPTION:
XS GIS Cut Line= 3
      1397404.99        6800488.      1397754.36      6800403.27
      1398073.92      6799994.32
#Sta/Elev= 30
  4640.5 2520.39  4643.1 2520.39  4650.8  2518.2  4671.4 2514.67  4742.4 2511.82
  4789.4 2507.25  4794.9 2506.03  4825.7 2502.87  4831.2 2501.65  4878.1 2499.46
  4897.8 2497.54    5000 2494.71  5015.7 2492.55  5016.2 2492.05  5022.2 2492.05
  5022.7 2492.55  5025.6 2494.46  5032.1 2496.53    5040  2501.6  5046.4 2506.52
  5054.5  2509.6  5060.8 2512.96  5082.8 2517.29  5089.8 2517.63  5096.1 2518.96
  5133.2 2521.97  5160.3 2524.91    5239 2528.75  5425.3 2529.64    5519 2531.38
#Mann= 3 ,-1 , 0
  4640.5     .07       0  5015.7     .07       0  5022.7     .07       0
Bank Sta=5015.7,5022.7
XS Rating Curve= 0 ,0
Exp/Cntr=0.3,0.1

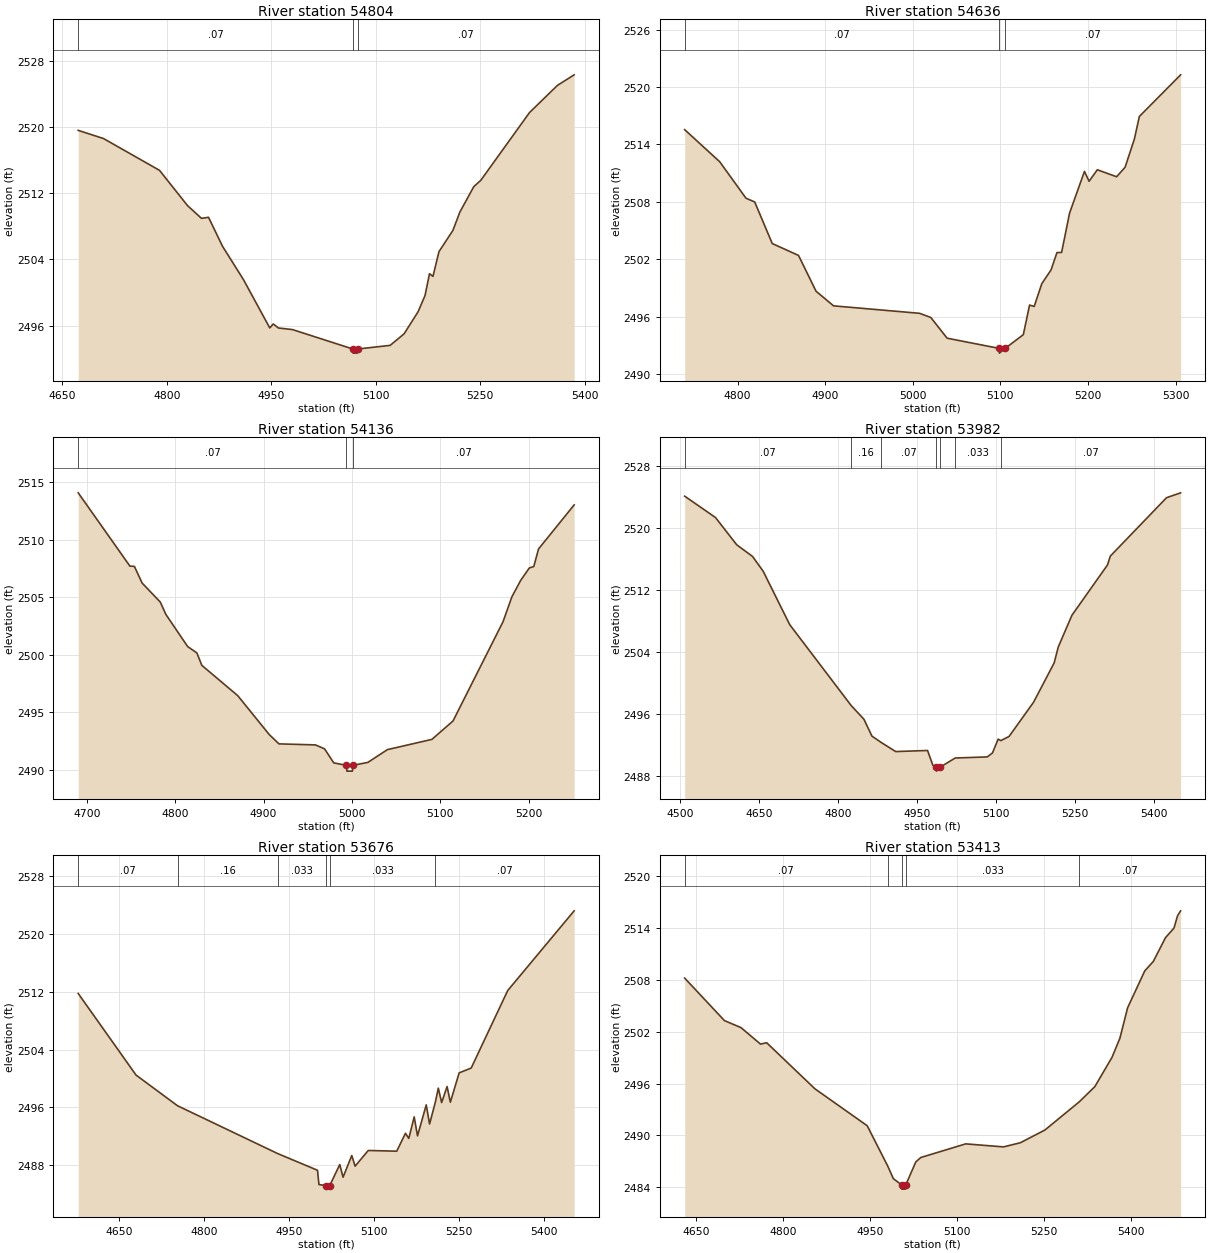
Type RM Length L Ch R = 1 ,54804   ,168,168,168
BEGIN DESCRIPTION:
Holder Creek 4434
END DESCRIPTION:
XS GIS Cut Line= 3
      1397358.85      6800626.73      1397684.48       6800657.7
      1398068.94      6800647.57
#Sta/Elev= 30
  4672.9 2519.62  4709.2 2518.63  4789.6 2514.78  4829.8 2510.51  4849.8 2508.97
  4859.9  2509.1    4880 2505.59  4910.1 2501.55  4947.8 2495.71  4952.8 2496.19
  4960.3  2495.7  4980.4 2495.51    5067 2493.16  5067.5 2492.66  5073.6 2492.66
  5074.1 2493.16  5120.6  2493.6  5140.6    2495  5160.6 2497.66  5170.6 2499.63
    5177 2502.27    5182 2501.95  5190.6 2504.94  5210.6 2507.51  5220.6 2509.73
  5240.6 2512.81  5250.6 2513.57  5320.6 2521.78  5360.6 2525.06  5384.6 2526.34
#Mann= 3 ,-1 , 0
  4672.9     .07       0    5067     .07       0  5074.1     .07       0
Bank Sta=5067,5074.1
XS Rating Curve= 0 ,0
Exp/Cntr=0.3,0.1

Type RM Length L Ch R = 1 ,54636   ,500,500,500
BEGIN DESCRIPTION:
Holder Creek 95.0
END DESCRIPTION:
XS GIS Cut Line= 3
      1397455.01        6800788.       1397715.5       6800786.5
      1398005.01        6800688.
#Sta/Elev= 30
  4739.5 2515.54  4779.5 2512.19  4809.5 2508.38  4819.5 2507.98  4839.5 2503.64
  4869.5  2502.4  4889.5 2498.66  4909.5 2497.13  5007.8 2496.35  5020.6 2495.91
  5039.2 2493.75  5098.4 2492.69  5098.9 2492.19  5105.5 2492.69  5126.2 2494.12
  5133.3 2497.21  5138.6 2497.07  5147.3 2499.45  5157.9 2500.89  5164.6  2502.7
  5169.9 2502.71    5179 2506.82    5196 2511.18  5201.3 2510.15  5210.7 2511.35
  5232.7 2510.62  5242.4 2511.61    5253 2514.56  5258.7 2516.92  5305.8 2521.27
#Mann= 3 ,-1 , 0
  4739.5     .07       0  5098.4     .07       0  5105.5     .07       0
Bank Sta=5098.4,5105.5
XS Rating Curve= 0 ,0
Exp/Cntr=0.3,0.1

Type RM Length L Ch R = 1 ,54136   ,154,154,154
BEGIN DESCRIPTION:
Holder Creek 94.0
END DESCRIPTION:
XS GIS Cut Line= 3
      1397454.99        6801138.        1397755.      6801215.27
      1398005.01        6801188.
#Sta/Elev= 30
  4690.2 2514.08  4748.7 2507.71  4753.8 2507.68  4762.5 2506.24  4783.1 2504.58
  4789.4 2503.51  4814.1 2500.71  4824.5 2500.16  4830.1 2499.08  4870.8 2496.44
  4906.3 2493.07  4917.4 2492.25  4958.7 2492.16    4969 2491.82  4979.4  2490.6
  4993.8 2490.38  4994.3 2489.88  5000.5 2489.88    5001 2490.38    5018 2490.64
  5040.2 2491.75  5090.5 2492.64  5114.4 2494.24    5171 2502.87  5181.1 2505.05
  5191.1 2506.48  5200.8 2507.55  5205.8 2507.67  5211.2  2509.2  5251.5 2513.03
#Mann= 3 ,-1 , 0
  4690.2     .07       0  4993.8     .07       0    5001     .07       0
Bank Sta=4993.8,5001
XS Rating Curve= 0 ,0
Exp/Cntr=0.3,0.1

Type RM Length L Ch R = 1 ,53982   ,306,306,306
BEGIN DESCRIPTION:
Holder Creek 4438
END DESCRIPTION:
XS GIS Cut Line= 3
      1397266.86      6801309.03      1397755.09      6801369.78
      1398188.72      6801246.53
#Sta/Elev= 30
    4508 2524.08  4566.6 2521.33  4606.9 2517.82  4637.1 2516.31  4657.3  2514.4
  4707.7 2507.53  4824.5 2497.11  4848.7 2495.35    4864 2493.17  4882.1 2492.33
  4909.2 2491.18  4969.7 2491.32  4979.8 2489.42  4986.2 2489.16  4986.7 2488.66
  4993.4 2489.16  5022.3 2490.35  5083.1 2490.49  5093.1    2491  5103.9 2492.78
  5109.1 2492.59  5124.7 2493.13  5171.3 2497.54  5210.4  2502.6  5218.2 2504.65
  5244.2 2508.74  5311.8 2515.22  5317.2 2516.36    5424 2523.88  5450.8 2524.51
#Mann= 7 ,-1 , 0
    4508     .07       0  4824.5     .16       0  4882.1     .07       0
  4986.2     .07       0  4993.4     .07       0  5022.3    .033       0
  5109.1     .07       0
Bank Sta=4986.2,4993.4
XS Rating Curve= 0 ,0
Exp/Cntr=0.3,0.1

Type RM Length L Ch R = 1 ,53676   ,263,263,263
BEGIN DESCRIPTION:
Holder Creek 93.0
END DESCRIPTION:
XS GIS Cut Line= 3
      1397405.04      6801538.01      1397818.63      6801624.79
      1398205.03      6801387.98
#Sta/Elev= 30
  4577.4 2511.78  4679.5 2500.49  4752.8 2496.24  4929.7 2489.62    5000 2487.31
  5002.5 2485.33  5014.4  2485.2  5014.9  2484.7  5021.6  2485.2  5039.3  2488.1
  5045.1 2486.35  5060.5 2489.35  5066.4 2487.88  5089.6 2490.05  5139.9 2489.95
  5155.3 2492.43  5161.2 2491.72  5170.7  2494.7  5176.6 2492.07    5192 2496.36
  5197.9 2493.72  5207.9 2496.68  5213.3 2498.68  5219.2 2496.68  5228.8  2498.9
  5234.6 2496.73  5250.1 2500.79  5271.4 2501.46  5335.9 2512.19  5453.2 2523.22
#Mann= 6 ,-1 , 0
  4577.4     .07       0  4752.8     .16       0  4929.7    .033       0
  5014.4    .033       0  5021.6    .033       0  5207.9     .07       0
Bank Sta=5014.4,5021.6
XS Rating Curve= 0 ,0
Exp/Cntr=0.3,0.1

Type RM Length L Ch R = 1 ,53413   ,234,234,234
BEGIN DESCRIPTION:
Holder Creek 4437
END DESCRIPTION:
XS GIS Cut Line= 3
      1397489.11      6801930.54      1397844.19      6801828.33
      1398240.38      6801547.19
#Sta/Elev= 30
  4630.5 2508.21  4699.1 2503.29  4727.6 2502.48  4761.3 2500.57  4771.9 2500.73
  4855.2 2495.39  4945.3 2491.12  4980.7 2486.45  4990.4 2484.99  5004.5 2484.28
    5005 2483.78  5011.4 2483.78  5011.9 2484.28  5029.1 2486.93  5037.7 2487.44
  5115.2 2489.02  5180.4 2488.67  5209.4 2489.15  5251.7 2490.62  5310.9 2493.88
  5337.9 2495.65  5367.4 2499.03  5381.1 2501.25  5394.4 2504.78    5424 2509.05
  5438.7 2510.14  5459.6 2512.88  5474.4 2514.01  5480.5 2515.43  5485.8    2516
#Mann= 5 ,-1 , 0
  4630.5     .07       0  4980.7    .033       0  5004.5    .033       0
  5011.9    .033       0  5310.9     .07       0
Bank Sta=5004.5,5011.9
XS Rating Curve= 0 ,0
Exp/Cntr=0.3,0.1

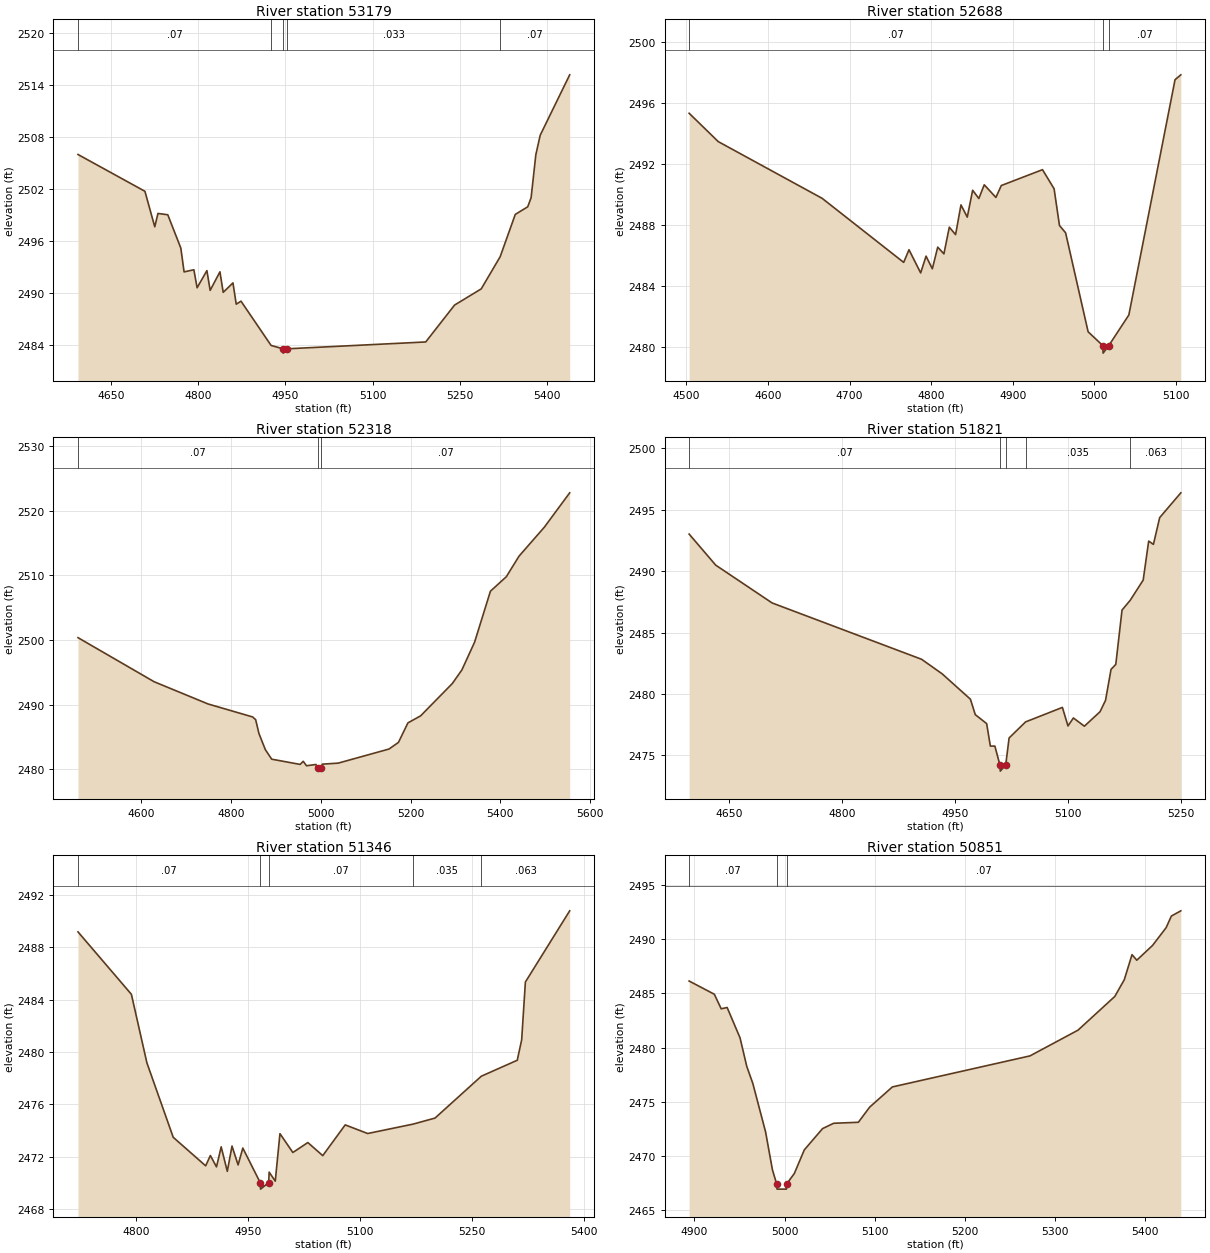
Type RM Length L Ch R = 1 ,53179   ,491,491,491
BEGIN DESCRIPTION:
Holder Creek 92.0
END DESCRIPTION:
XS GIS Cut Line= 3
      1397614.07      6802192.71      1397978.18      6802011.96
      1398355.04      6801787.98
#Sta/Elev= 30
  4593.5    2506  4708.5 2501.75  4725.4 2497.65  4730.9 2499.19  4747.8 2499.04
  4770.2 2495.19  4775.8 2492.44  4792.6 2492.69  4798.2 2490.61    4815 2492.59
  4820.6 2490.31  4837.4 2492.45    4843 2490.08  4859.8 2491.17  4865.4 2488.71
  4873.6 2489.06  4925.3 2483.95  4945.7 2483.56  4946.2 2483.06  4953.1 2483.56
    5191 2484.35  5240.6 2488.61  5286.4 2490.48  5318.9 2494.19  5344.9 2499.08
  5366.3 2499.96  5372.1 2501.01  5380.2 2505.96  5387.7 2508.22  5438.4  2515.2
#Mann= 5 ,-1 , 0
  4593.5     .07       0  4925.3    .033       0  4945.7    .033       0
  4953.1    .033       0  5318.9     .07       0
Bank Sta=4945.7,4953.1
XS Rating Curve= 0 ,0
Exp/Cntr=0.3,0.1

Type RM Length L Ch R = 1 ,52688   ,370,370,370
BEGIN DESCRIPTION:
Holder Creek 91.0
END DESCRIPTION:
XS GIS Cut Line= 3
      1397954.99      6802538.01      1398331.74      6802214.64
      1398404.98      6802138.02
#Sta/Elev= 30
  4503.5 2495.35  4539.2 2493.49  4666.5 2489.77  4766.4 2485.57  4772.9  2486.4
  4787.2 2484.88  4793.8 2485.98  4801.5 2485.15  4808.1 2486.57  4815.7 2486.13
  4822.3 2487.88    4830 2487.39  4836.6 2489.34  4844.3 2488.54  4850.9  2490.3
  4858.5 2489.76  4865.1 2490.66  4879.4 2489.83    4886 2490.61  4936.5 2491.65
  4950.7  2490.4  4957.3 2487.99  4964.8 2487.51  4992.4 2481.02  5010.3 2480.12
  5010.8 2479.62  5017.8 2480.12  5042.3 2482.12  5098.9 2497.55    5106 2497.87
#Mann= 3 ,-1 , 0
  4503.5     .07       0  5010.3     .07       0  5017.8     .07       0
Bank Sta=5010.3,5017.8
XS Rating Curve= 0 ,0
Exp/Cntr=0.3,0.1

Type RM Length L Ch R = 1 ,52318   ,497,497,497
BEGIN DESCRIPTION:
Holder Creek 90.0
END DESCRIPTION:
XS GIS Cut Line= 3
      1398005.03      6802887.98      1398405.13      6802522.94
      1398804.96      6802138.03
#Sta/Elev= 30
  4458.4 2500.37  4628.3 2493.54  4748.5  2490.1  4847.9 2488.09  4854.6 2487.67
    4862 2485.52  4876.2 2483.03  4890.4 2481.55  4953.9 2480.74  4960.7 2481.22
  4968.1 2480.53  4989.1 2480.73  4992.6  2480.2  4993.1  2479.7  4999.8  2479.7
  5000.3  2480.2  5003.4 2480.78  5038.8 2480.94    5152 2483.12  5173.1 2484.15
  5194.2 2487.17  5222.5 2488.26  5293.3 2493.27  5314.6 2495.38  5342.9 2499.67
  5378.2 2507.56  5413.7 2509.81    5442 2512.99  5498.6 2517.49    5555  2522.8
#Mann= 3 ,-1 , 0
  4458.4     .07       0  4992.6     .07       0  5000.3     .07       0
Bank Sta=4992.6,5000.3
XS Rating Curve= 0 ,0
Exp/Cntr=0.3,0.1

Type RM Length L Ch R = 1 ,51821   ,475,475,475
BEGIN DESCRIPTION:
Holder Creek 89.0
END DESCRIPTION:
XS GIS Cut Line= 3
      1398304.98      6803038.01       1398654.7      6802838.15
      1398854.98      6802688.02
#Sta/Elev= 30
  4597.2 2493.02  4632.5 2490.49  4707.4 2487.41    4906 2482.82  4933.4 2481.63
  4970.8 2479.57  4977.3 2478.31  4992.4 2477.58  4997.3 2475.75  5003.3 2475.75
    5010 2474.21  5010.5 2473.71  5017.7 2474.21  5022.2 2476.41  5044.1 2477.72
    5093  2478.9  5100.4 2477.39  5107.6 2478.04  5122.2 2477.37    5143 2478.55
  5150.3 2479.48  5157.6    2482  5163.9  2482.4  5172.2 2486.83    5183 2487.62
  5200.3 2489.27  5207.6 2492.45  5213.9 2492.18  5222.2 2494.36  5250.3 2496.38
#Mann= 5 ,-1 , 0
  4597.2     .07       0    5010     .07       0  5017.7     .07       0
  5044.1    .035       0    5183    .063       0
Bank Sta=5010,5017.7
XS Rating Curve= 0 ,0
Exp/Cntr=0.3,0.1

Type RM Length L Ch R = 1 ,51346   ,495,495,495
BEGIN DESCRIPTION:
Holder Creek 88.0
END DESCRIPTION:
XS GIS Cut Line= 3
      1399055.01      6803388.01      1398884.97      6803168.08
        1398855.      6802787.96
#Sta/Elev= 30
    4722 2489.17  4793.6  2484.4  4814.4 2479.16  4849.7 2473.47  4893.2 2471.29
  4899.5 2472.08  4907.7 2471.21    4914 2472.74  4922.2 2470.87  4928.5  2472.8
  4936.7 2471.36    4943 2472.65  4966.3 2470.01  4966.8 2469.51  4977.7 2470.01
  4978.3 2470.81  4986.5 2470.12  4992.8 2473.75  5010.1 2472.31  5030.2 2473.07
  5050.2 2472.07  5080.3 2474.42  5110.4 2473.76  5171.4 2474.48  5200.7 2474.94
  5262.8 2478.14    5311 2479.36  5316.9 2480.92  5321.9 2485.34  5381.3 2490.78
#Mann= 5 ,-1 , 0
    4722     .07       0  4966.3     .07       0  4977.7     .07       0
  5171.4    .035       0  5262.8    .063       0
Bank Sta=4966.3,4977.7
XS Rating Curve= 0 ,0
Exp/Cntr=0.3,0.1

Type RM Length L Ch R = 1 ,50851   ,499,499,499
BEGIN DESCRIPTION:
Holder Creek 87.0
END DESCRIPTION:
XS GIS Cut Line= 3
        1399355.      6803137.99      1399285.16      6803058.38
      1399154.99      6802637.97
#Sta/Elev= 30
  4894.1 2486.13  4922.1 2484.91  4929.7 2483.57  4936.3 2483.69  4950.6  2480.9
  4958.1 2478.26  4964.8  2476.7    4979 2472.22  4986.6 2468.73  4991.2 2467.45
  4991.7 2466.95  5002.1 2466.95  5002.6 2467.45  5010.9 2468.39    5022 2470.57
  5042.3 2472.53  5054.6 2473.02    5082 2473.11  5094.6 2474.51  5119.8 2476.37
  5272.6 2479.23  5325.9  2481.6  5366.8 2484.71  5377.3 2486.25  5385.9 2488.56
  5391.2 2488.05  5408.7 2489.41  5423.8 2491.05  5429.6 2492.12  5440.1  2492.6
#Mann= 3 ,-1 , 0
  4894.1     .07       0  4991.2     .07       0  5002.6     .07       0
Bank Sta=4991.2,5002.6
XS Rating Curve= 0 ,0
Exp/Cntr=0.3,0.1

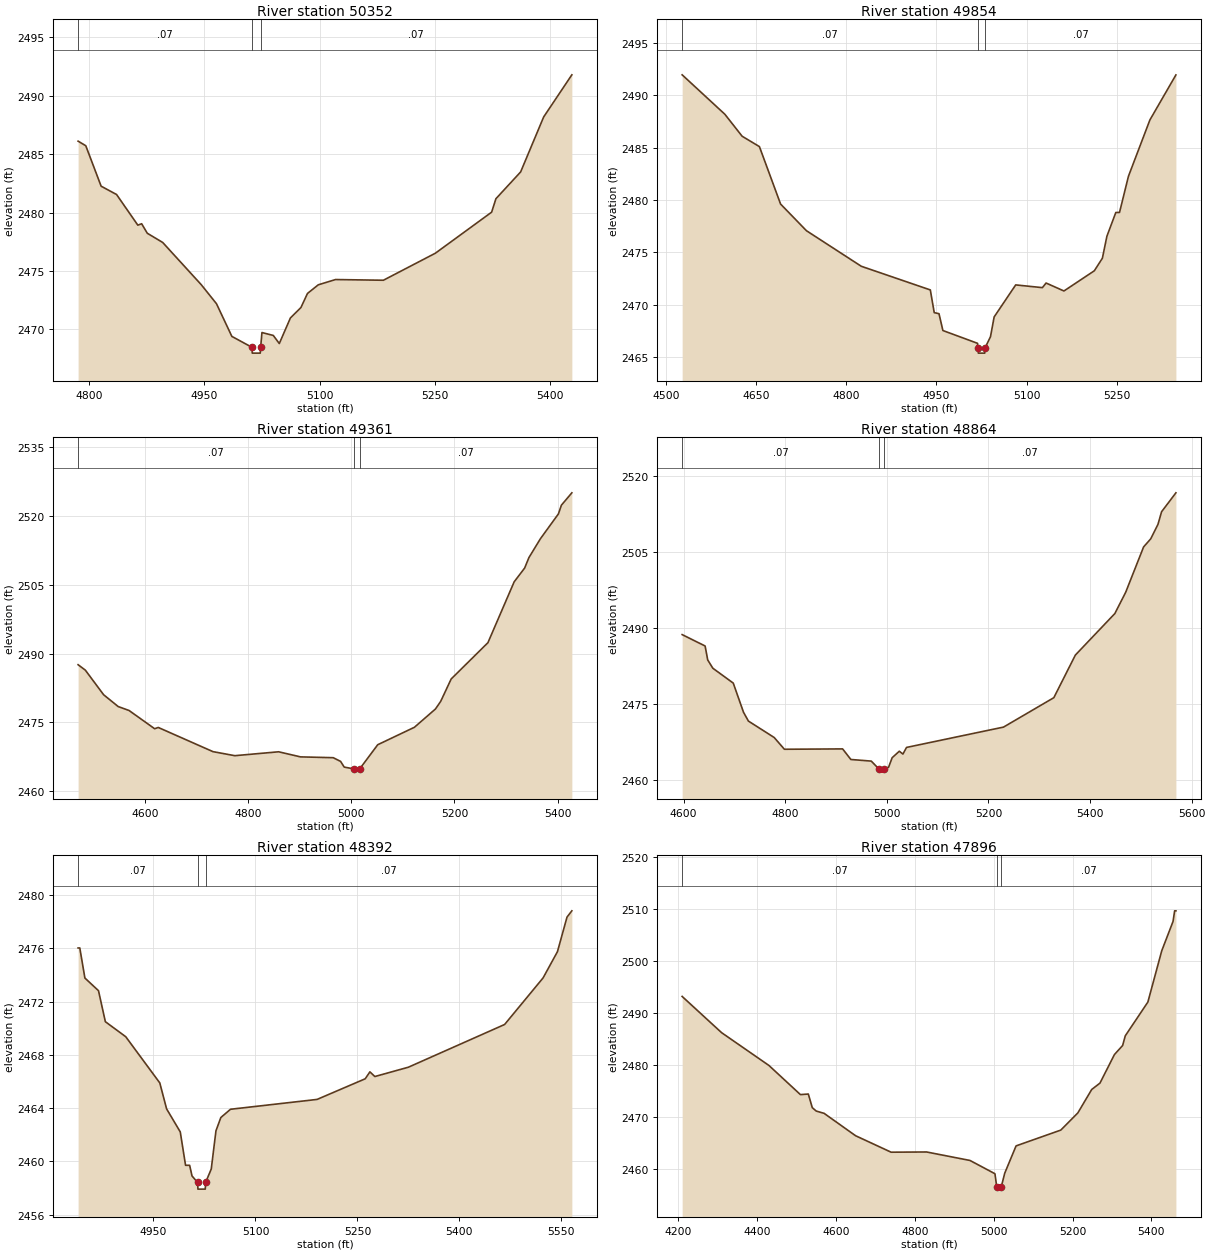
Type RM Length L Ch R = 1 ,50352   ,498,498,498
BEGIN DESCRIPTION:
Holder Creek 86.0
END DESCRIPTION:
XS GIS Cut Line= 3
        1399705.      6803087.96      1399691.68      6802873.77
      1399504.98      6802487.97
#Sta/Elev= 30
  4785.4  2486.1  4795.4 2485.71  4815.4 2482.25  4835.5 2481.54  4863.2 2478.92
  4868.2 2479.04  4875.5 2478.23  4895.6 2477.44  4945.7 2473.84  4965.7  2472.2
  4985.7 2469.41  5011.8 2468.48  5012.3 2467.98  5022.7 2467.98  5023.2 2468.48
  5024.9 2469.74  5039.7 2469.49  5047.5  2468.8    5062 2470.99  5075.7 2471.88
  5084.2 2473.08  5098.3 2473.82  5120.8 2474.27  5183.1 2474.21  5250.8 2476.52
  5324.1 2480.03  5329.7 2481.18  5361.9 2483.47  5391.9 2488.17  5428.6 2491.77
#Mann= 3 ,-1 , 0
  4785.4     .07       0  5011.8     .07       0  5023.2     .07       0
Bank Sta=5011.8,5023.2
XS Rating Curve= 0 ,0
Exp/Cntr=0.3,0.1

Type RM Length L Ch R = 1 ,49854   ,493,493,493
BEGIN DESCRIPTION:
Holder Creek 85.0
END DESCRIPTION:
XS GIS Cut Line= 3
        1400355.        6802988.      1400054.79      6802622.88
      1399854.97      6802337.96
#Sta/Elev= 30
  4527.3 2491.97  4598.3  2488.2    4627  2486.1  4655.7 2485.11  4690.9 2479.62
  4733.9 2477.07  4825.1 2473.67  4939.8 2471.41  4946.3 2469.24  4954.2 2469.14
  4960.7 2467.53  5018.2 2466.31  5019.2 2465.87  5019.7 2465.37  5030.3 2465.37
  5030.8 2465.87  5039.8 2466.94  5045.9 2468.83  5081.7 2471.89  5126.1 2471.63
  5132.2 2472.07  5161.9 2471.31  5212.4 2473.24  5225.8 2474.44  5233.3 2476.54
  5248.1 2478.81  5254.3 2478.82  5269.1 2482.27  5304.8 2487.66    5348 2491.96
#Mann= 3 ,-1 , 0
  4527.3     .07       0  5019.2     .07       0  5030.8     .07       0
Bank Sta=5019.2,5030.8
XS Rating Curve= 0 ,0
Exp/Cntr=0.3,0.1

Type RM Length L Ch R = 1 ,49361   ,497,497,497
BEGIN DESCRIPTION:
Holder Creek 84.0
END DESCRIPTION:
XS GIS Cut Line= 3
        1400805.        6802738.      1400435.07      6802358.17
      1400355.01      6801938.03
#Sta/Elev= 30
  4469.8 2487.58  4483.8  2486.4  4519.3 2481.03  4547.6 2478.45  4568.7 2477.59
  4618.3 2473.61  4625.3 2473.89  4731.5 2468.61  4773.9 2467.73  4858.8 2468.58
  4901.2 2467.47  4964.8 2467.29    4979 2466.49  4986.1 2465.24  5004.5 2464.86
    5005 2464.36  5016.2 2464.86  5051.1 2470.12  5122.3 2473.93  5163.1 2477.92
  5173.2 2479.57  5193.6 2484.47  5264.9 2492.39  5315.8 2505.67  5336.1 2508.67
  5344.4 2510.95  5366.7 2515.07  5401.7  2520.5  5407.4 2522.39  5427.7 2525.09
#Mann= 3 ,-1 , 0
  4469.8     .07       0  5004.5     .07       0  5016.2     .07       0
Bank Sta=5004.5,5016.2
XS Rating Curve= 0 ,0
Exp/Cntr=0.3,0.1

Type RM Length L Ch R = 1 ,48864   ,472,472,472
BEGIN DESCRIPTION:
Holder Creek 83.0
END DESCRIPTION:
XS GIS Cut Line= 3
        1400955.      6802688.03       1400910.2      6802287.52
      1400505.03      6801888.03
#Sta/Elev= 30
    4597 2488.67  4642.2 2486.42  4647.3 2483.67  4657.4 2482.03  4697.6 2479.09
  4717.8 2473.33  4727.4 2471.59  4778.1 2468.35  4798.3 2466.02  4912.9 2466.09
  4929.1    2464  4969.3 2463.68  4983.6  2462.2  4984.1  2461.7  4995.3  2462.2
  5003.4 2462.47  5010.4 2464.35  5024.5 2465.63  5031.6 2465.07  5038.7 2466.38
  5229.7  2470.4  5328.7 2476.21  5371.1 2484.63  5448.8 2492.83  5470.1 2497.02
  5505.4 2505.99  5519.5  2507.6  5533.7 2510.45  5540.8 2512.94    5569 2516.68
#Mann= 3 ,-1 , 0
    4597     .07       0  4983.6     .07       0  4995.3     .07       0
Bank Sta=4983.6,4995.3
XS Rating Curve= 0 ,0
Exp/Cntr=0.3,0.1

Type RM Length L Ch R = 1 ,48392   ,496,496,496
BEGIN DESCRIPTION:
Holder Creek 82.0
END DESCRIPTION:
XS GIS Cut Line= 3
        1401305.      6802437.98      1401315.06      6802277.39
      1400904.99      6801887.99
#Sta/Elev= 30
  4839.1 2476.04  4841.6 2476.04  4849.1 2473.78  4869.1 2472.83  4879.2  2470.5
  4909.2 2469.37  4959.3  2465.9  4969.3 2463.95  4989.4 2462.22  4997.2 2459.71
  5003.2 2459.71  5006.7 2458.91  5014.9 2458.42  5015.4 2457.92  5026.2 2457.92
  5026.7 2458.42    5035 2459.43  5041.9  2462.3  5049.1  2463.3  5063.3 2463.92
  5190.7 2464.66  5261.5 2466.21  5268.4 2466.73  5275.7 2466.38    5325 2467.08
  5466.6 2470.29  5523.2 2473.79  5544.3 2475.76  5558.4 2478.36  5565.5 2478.83
#Mann= 3 ,-1 , 0
  4839.1     .07       0  5014.9     .07       0  5026.7     .07       0
Bank Sta=5014.9,5026.7
XS Rating Curve= 0 ,0
Exp/Cntr=0.3,0.1

Type RM Length L Ch R = 1 ,47896   ,458,458,458
BEGIN DESCRIPTION:
Holder Creek 81.0
END DESCRIPTION:
XS GIS Cut Line= 3
        1401555.      6802687.99      1401544.96      6801897.86
      1401255.02      6801538.03
#Sta/Elev= 30
  4209.8 2493.23  4309.8 2486.27  4429.8 2479.97  4509.8 2474.36  4529.8 2474.47
  4539.8 2471.86  4549.8  2471.2  4569.8 2470.76  4649.8 2466.45  4739.8 2463.29
  4829.8 2463.33  4939.9  2461.7  5003.1 2459.15  5007.6 2456.69  5008.1 2456.19
  5019.4 2456.69  5027.9 2459.24  5056.7  2464.5  5170.2 2467.54  5213.4 2470.84
  5248.6 2475.35  5269.5 2476.57  5306.2 2482.06    5327  2483.8  5333.7 2485.66
    5391 2492.15  5426.2 2502.01  5454.9 2507.66  5458.9 2509.69  5462.1 2509.69
#Mann= 3 ,-1 , 0
  4209.8     .07       0  5007.6     .07       0  5019.4     .07       0
Bank Sta=5007.6,5019.4
XS Rating Curve= 0 ,0
Exp/Cntr=0.3,0.1