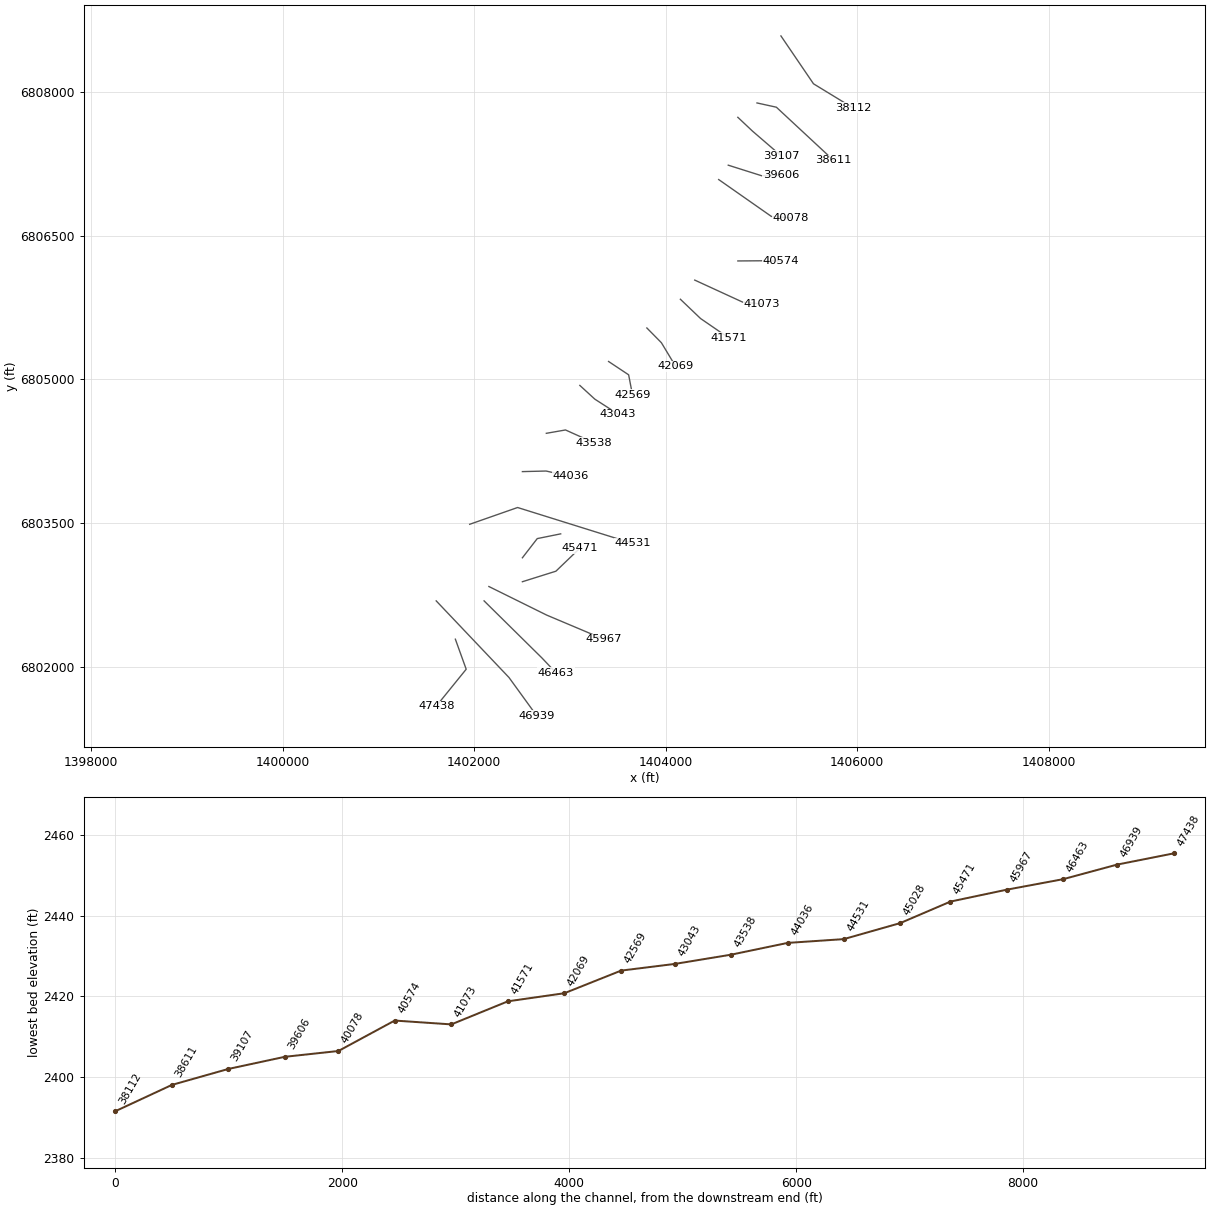
HEC-RAS study Holder Creek.prj: Holder Creek Base Level Engineering

--- Holder Creek.g01 (geometry) --- (continued)

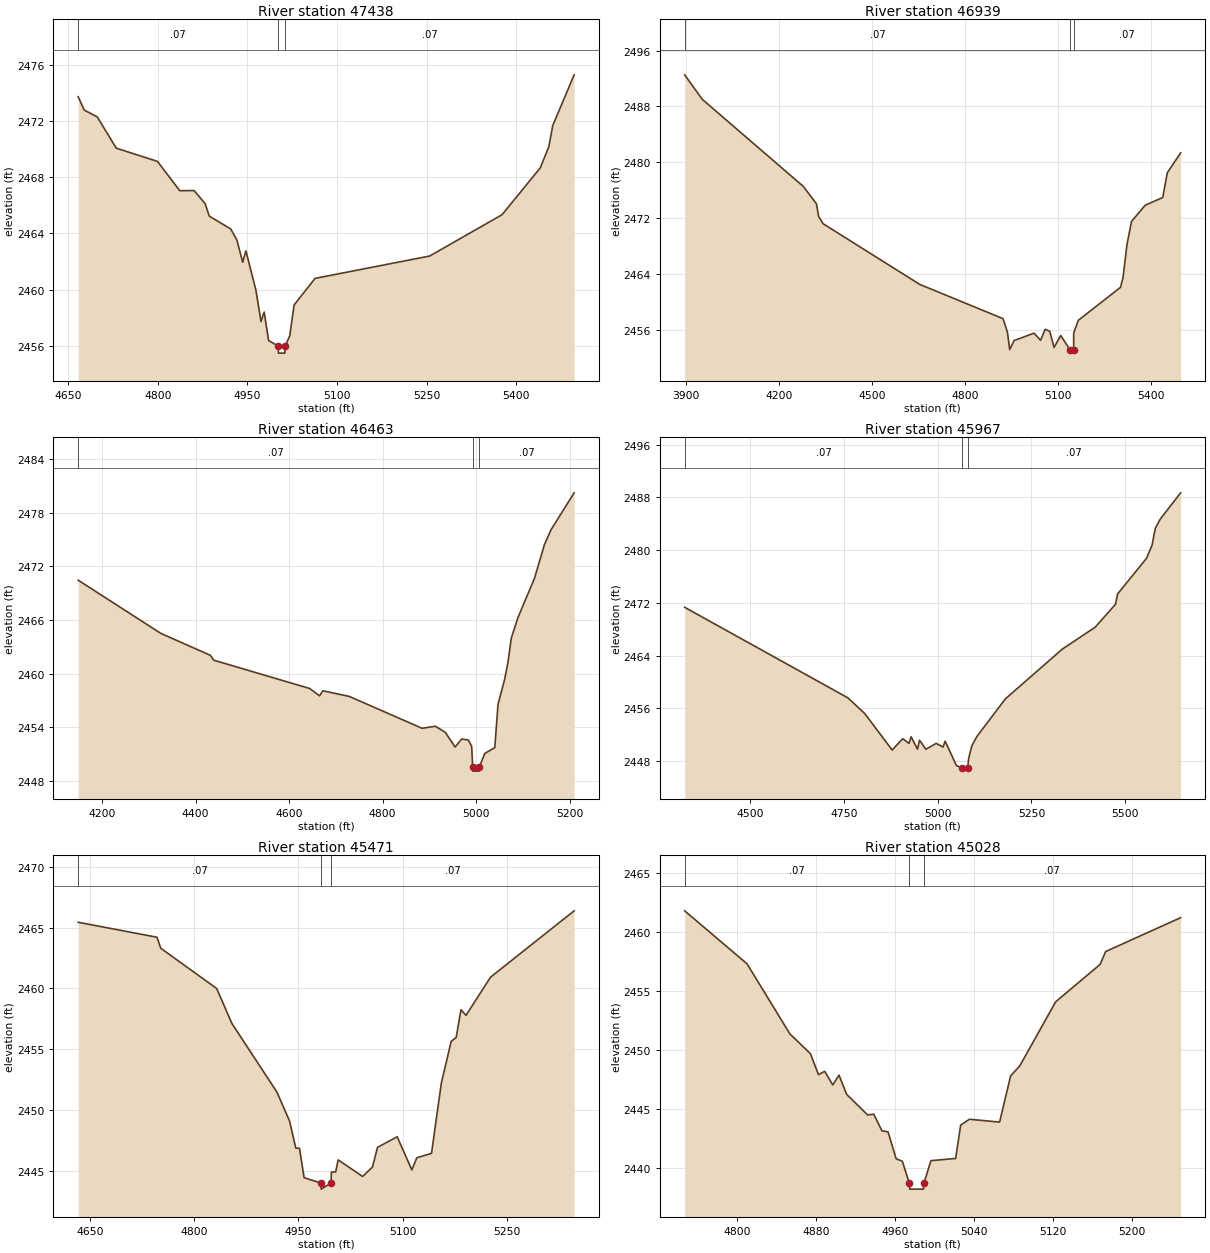
Type RM Length L Ch R = 1 ,47438   ,499,499,499
BEGIN DESCRIPTION:
Holder Creek 80.0
END DESCRIPTION:
XS GIS Cut Line= 3
      1401805.01      6802287.97      1401918.13      6801974.24
      1401605.02      6801588.02
#Sta/Elev= 30
  4666.5 2473.75  4676.5  2472.8  4698.4 2472.31  4730.3 2470.08  4799.2 2469.14
  4836.6 2467.05  4860.6 2467.06  4879.1 2466.13    4886 2465.24    4922 2464.32
  4932.2 2463.54    4942 2461.95  4947.4 2462.76  4964.1 2459.97  4972.7 2457.72
    4978  2458.4  4985.4 2456.37  5001.4 2455.97  5001.9 2455.47  5012.7 2455.47
  5013.2 2455.97  5020.9 2456.72  5028.1  2458.9  5063.3  2460.8  5255.1 2462.39
  5376.5 2465.34  5440.5 2468.68  5454.8 2470.19  5461.3 2471.69  5497.2 2475.31
#Mann= 3 ,-1 , 0
  4666.5     .07       0  5001.4     .07       0  5013.2     .07       0
Bank Sta=5001.4,5013.2
XS Rating Curve= 0 ,0
Exp/Cntr=0.3,0.1

Type RM Length L Ch R = 1 ,46939   ,476,476,476
BEGIN DESCRIPTION:
Holder Creek 79.0
END DESCRIPTION:
XS GIS Cut Line= 3
      1401604.98      6802688.02      1402364.97      6801887.94
      1402654.98      6801488.03
#Sta/Elev= 30
  3896.5 2492.52    3953 2489.02  4278.6 2476.55    4321 2474.06  4327.9 2472.25
  4342.1 2471.22  4653.5 2462.53  4922.1 2457.62  4936.3 2455.66  4943.5 2453.19
  4957.7 2454.49    5022 2455.55  5042.9 2454.52  5057.6  2456.1  5072.3 2455.82
  5086.4 2453.51  5107.8 2455.21  5137.5 2453.19    5138 2452.69  5149.4 2453.19
  5149.6 2455.56  5164.3 2457.38  5300.4 2462.11  5308.7 2463.54  5321.2 2468.23
  5335.9 2471.54    5380 2473.86  5436.4 2474.96  5451.1  2478.5    5494 2481.35
#Mann= 3 ,-1 , 0
  3896.5     .07       0  5137.5     .07       0  5149.4     .07       0
Bank Sta=5137.5,5149.4
XS Rating Curve= 0 ,0
Exp/Cntr=0.3,0.1

Type RM Length L Ch R = 1 ,46463   ,496,496,496
BEGIN DESCRIPTION:
Holder Creek 78.0
END DESCRIPTION:
XS GIS Cut Line= 3
      1402105.02      6802687.98      1402710.81      6802090.31
      1402854.98      6801938.02
#Sta/Elev= 30
    4149 2470.46  4325.8  2464.5  4431.8 2462.04  4438.9  2461.5  4643.9 2458.33
  4665.2 2457.51  4672.2 2458.07  4728.8 2457.44  4884.4 2453.87  4912.7  2454.1
  4933.9 2453.43  4955.1 2451.77  4969.2 2452.67  4983.4 2452.55  4990.5 2451.84
  4992.7 2449.57  4993.2 2449.07  5006.7 2449.07  5007.2 2449.57  5018.6 2451.05
    5040 2451.71  5046.9 2456.56  5061.1 2459.36  5068.3  2461.3  5075.2 2463.96
  5089.4 2466.26    5125 2470.69    5146 2474.42  5160.2 2476.11  5209.7 2480.25
#Mann= 3 ,-1 , 0
    4149     .07       0  4992.7     .07       0  5007.2     .07       0
Bank Sta=4992.7,5007.2
XS Rating Curve= 0 ,0
Exp/Cntr=0.3,0.1

Type RM Length L Ch R = 1 ,45967   ,496,496,496
BEGIN DESCRIPTION:
Holder Creek 77.0
END DESCRIPTION:
XS GIS Cut Line= 3
      1402155.01        6802838.      1402758.78      6802539.57
      1403354.98      6802288.01
#Sta/Elev= 30
  4326.5 2471.33  4761.3 2457.58  4806.1  2455.2    4879 2449.67  4907.1 2451.39
  4923.9 2450.67  4929.5 2451.68  4946.4 2449.81  4951.9 2451.15  4968.8 2449.79
  4996.1 2450.68  5014.5 2450.12    5020 2451.02  5050.2 2447.31  5065.6 2446.97
  5066.1 2446.47  5080.1 2446.97  5082.7  2448.4  5091.1  2450.3  5104.4 2451.71
  5180.4 2457.43  5332.4    2465  5419.2 2468.29  5473.5 2471.77  5479.4 2473.36
    5556 2478.74  5571.1 2480.76  5579.7 2483.32  5592.9 2484.71  5647.1  2488.7
#Mann= 3 ,-1 , 0
  4326.5     .07       0  5065.6     .07       0  5080.1     .07       0
Bank Sta=5065.6,5080.1
XS Rating Curve= 0 ,0
Exp/Cntr=0.3,0.1

Type RM Length L Ch R = 1 ,45471   ,443,443,443
BEGIN DESCRIPTION:
Holder Creek 76.0
END DESCRIPTION:
XS GIS Cut Line= 3
      1402504.98        6802888.      1402855.01        6802998.
      1403105.04      6803238.03
#Sta/Elev= 30
  4633.1 2465.44  4746.5 2464.21  4751.8 2463.31  4832.3    2460  4854.2 2457.13
    4919 2451.49  4937.1 2449.12  4946.2 2446.88  4951.4 2446.88  4958.1 2444.46
  4982.2 2444.02  4982.7 2443.52  4996.8 2444.02  4997.4 2444.93  5003.5 2444.93
  5007.1 2445.92  5042.3 2444.56  5056.5 2445.34  5063.7 2446.95    5092 2447.82
  5113.1  2445.1  5120.3  2446.1  5141.4 2446.46  5155.5 2452.22  5169.7 2455.66
  5176.9 2455.98  5183.8 2458.26    5191 2457.79  5226.3 2460.93  5346.6 2466.38
#Mann= 3 ,-1 , 0
  4633.1     .07       0  4982.2     .07       0  4996.8     .07       0
Bank Sta=4982.2,4996.8
XS Rating Curve= 0 ,0
Exp/Cntr=0.3,0.1

Type RM Length L Ch R = 1 ,45028   ,497,497,497
BEGIN DESCRIPTION:
Holder Creek 75.0
END DESCRIPTION:
XS GIS Cut Line= 3
      1402505.02      6803138.02       1402660.2      6803338.47
      1402905.03      6803388.01
#Sta/Elev= 30
  4746.5 2461.76  4809.8 2457.27  4853.3 2451.33  4874.1 2449.66  4882.3 2447.88
  4888.6 2448.16  4896.8 2447.01  4903.1 2447.84  4910.9 2446.21  4932.1 2444.47
  4938.4 2444.53  4946.6 2443.13  4952.9 2443.03  4961.1 2440.75  4967.4 2440.54
  4974.5 2438.68    4975 2438.18  4988.8 2438.18  4989.3 2438.68  4996.4 2440.59
  5021.5 2440.78  5026.6 2443.61  5035.5  2444.1  5066.1 2443.86  5077.3 2447.78
  5086.5 2448.61    5123 2454.05  5168.1 2457.22  5173.7 2458.31  5249.8 2461.18
#Mann= 3 ,-1 , 0
  4746.5     .07       0  4974.5     .07       0  4989.3     .07       0
Bank Sta=4974.5,4989.3
XS Rating Curve= 0 ,0
Exp/Cntr=0.3,0.1

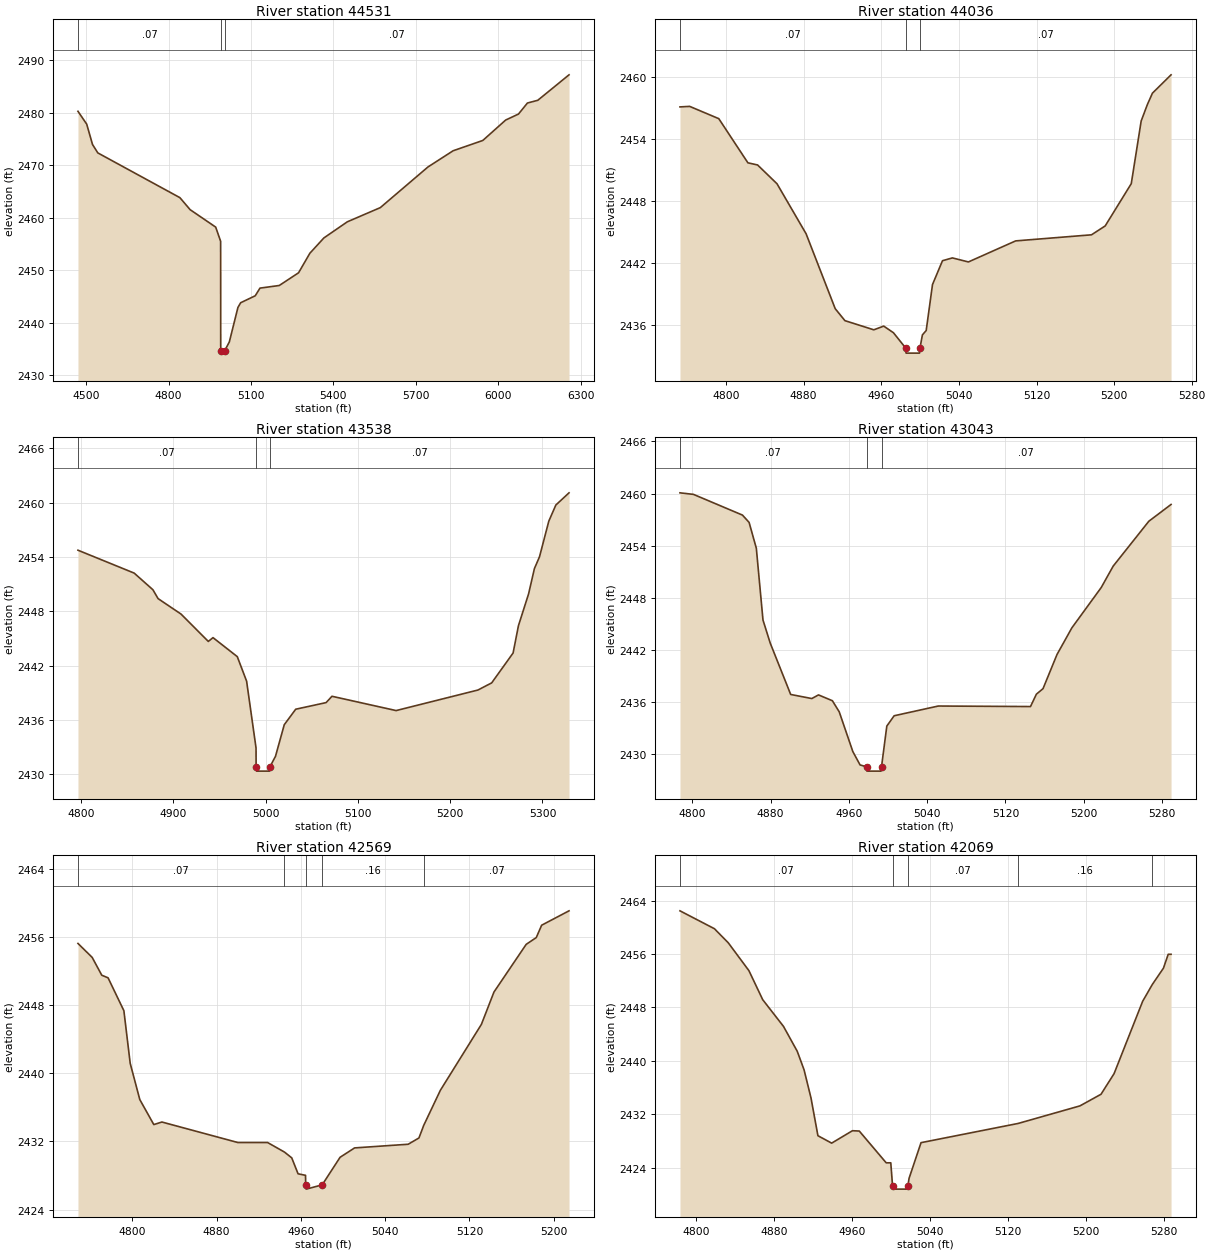
Type RM Length L Ch R = 1 ,44531   ,495,495,495
BEGIN DESCRIPTION:
Holder Creek 74.0
END DESCRIPTION:
XS GIS Cut Line= 3
      1401954.97      6803487.99      1402454.79      6803663.09
      1403655.04      6803287.99
#Sta/Elev= 30
  4470.4 2480.26  4502.2 2477.82  4523.4 2473.94  4542.7 2472.34  4841.3 2463.82
  4878.6 2461.53  4971.6 2458.21  4989.6 2455.51  4989.9 2434.71  4990.4 2434.21
  5004.7 2434.71  5021.2 2436.33  5052.6 2442.92  5062.6 2443.81  5115.5 2445.13
  5132.8 2446.59    5203 2447.09  5273.2 2449.51  5314.5 2453.24  5365.4 2456.15
  5450.7 2459.22  5570.7 2461.92  5744.1 2469.66  5835.8 2472.75  5943.7 2474.71
    6027  2478.6  6073.6 2479.74  6106.1 2481.84  6143.8 2482.36  6257.5 2487.21
#Mann= 3 ,-1 , 0
  4470.4     .07       0  4989.9     .07       0  5004.7     .07       0
Bank Sta=4989.9,5004.7
XS Rating Curve= 0 ,0
Exp/Cntr=0.3,0.1

Type RM Length L Ch R = 1 ,44036   ,498,498,498
BEGIN DESCRIPTION:
Holder Creek 73.0
END DESCRIPTION:
XS GIS Cut Line= 3
      1402505.04        6804038.      1402752.47      6804044.05
      1403005.02        6803988.
#Sta/Elev= 30
  4752.5 2457.14  4762.5 2457.19  4792.5    2456  4822.5 2451.72  4832.5 2451.51
  4852.5 2449.69  4882.5 2444.84  4912.5 2437.58  4922.5 2436.42  4952.3 2435.53
  4962.5 2435.89  4972.5 2435.25  4985.1 2433.77  4985.6 2433.27  4999.4 2433.27
  4999.9 2433.77  5002.4 2435.04  5006.3 2435.46  5012.8 2439.92  5023.1 2442.23
  5033.3  2442.5  5049.8 2442.11  5098.5 2444.15  5176.7 2444.74  5190.8  2445.6
  5217.7  2449.7  5227.9 2455.77  5234.3 2457.37  5239.5 2458.47  5258.7 2460.25
#Mann= 3 ,-1 , 0
  4752.5     .07       0  4985.1     .07       0  4999.9     .07       0
Bank Sta=4985.1,4999.9
XS Rating Curve= 0 ,0
Exp/Cntr=0.3,0.1

Type RM Length L Ch R = 1 ,43538   ,495,495,495
BEGIN DESCRIPTION:
Holder Creek 72.0
END DESCRIPTION:
XS GIS Cut Line= 3
      1402754.98        6804438.      1402955.15      6804472.94
      1403254.99      6804338.01
#Sta/Elev= 30
  4796.8 2454.76  4857.7 2452.23    4878 2450.39  4883.6 2449.41  4908.5  2447.7
    4938 2444.68  4943.1  2445.1  4969.4    2443  4979.5 2440.29  4989.7 2432.92
  4989.8 2430.85  4990.3 2430.35  5004.4 2430.35  5004.9 2430.85  5010.8 2431.99
  5020.3 2435.48  5032.7 2437.19  5065.6 2437.92    5072 2438.62  5141.5 2437.04
  5230.1 2439.31    5245  2440.1  5268.2  2443.4    5274 2446.42    5285 2449.94
  5291.3 2452.73  5296.8 2454.03  5306.9 2457.97  5314.5 2459.75  5328.8  2461.1
#Mann= 3 ,-1 , 0
  4796.8     .07       0  4989.8     .07       0  5004.9     .07       0
Bank Sta=4989.8,5004.9
XS Rating Curve= 0 ,0
Exp/Cntr=0.3,0.1

Type RM Length L Ch R = 1 ,43043   ,474,474,474
BEGIN DESCRIPTION:
Holder Creek 71.0
END DESCRIPTION:
XS GIS Cut Line= 3
      1403105.02      6804937.98      1403261.76      6804794.49
      1403504.97      6804638.02
#Sta/Elev= 30
  4787.5 2460.08  4801.3  2459.9  4851.3 2457.52  4858.1 2456.68  4865.5  2453.7
  4872.3 2445.44  4879.7 2442.79  4900.6 2436.88  4922.2 2436.41    4929 2436.83
  4943.2 2436.16  4950.2 2434.88  4964.1 2430.31  4971.5 2428.77  4978.1 2428.56
  4978.6 2428.06  4992.9 2428.06  4993.4 2428.56  4998.8 2433.24  5006.3 2434.43
  5051.4 2435.55  5145.6 2435.49  5151.6 2436.91  5158.4 2437.55  5172.7 2441.48
  5187.9 2444.55  5217.9 2449.19  5230.1 2451.65  5266.5 2456.81  5289.2 2458.74
#Mann= 3 ,-1 , 0
  4787.5     .07       0  4978.1     .07       0  4993.4     .07       0
Bank Sta=4978.1,4993.4
XS Rating Curve= 0 ,0
Exp/Cntr=0.3,0.1

Type RM Length L Ch R = 1 ,42569   ,500,500,500
BEGIN DESCRIPTION:
Holder Creek 70.0
END DESCRIPTION:
XS GIS Cut Line= 3
      1403404.99      6805188.01      1403614.68      6805048.78
        1403655.      6804838.01
#Sta/Elev= 30
  4748.3 2455.25  4761.8 2453.61  4770.9 2451.52  4776.9 2451.21  4791.9 2447.35
  4797.9 2441.17    4807 2436.92  4820.3 2433.98    4828 2434.28  4900.2 2431.87
  4928.4 2431.87  4944.4 2430.75  4951.3 2430.07  4957.3  2428.2  4964.4 2428.02
  4964.5  2426.9    4965  2426.4  4980.2  2426.9  4997.2 2430.14    5011 2431.24
  5061.9 2431.67  5072.1 2432.41  5076.6 2433.88  5092.4    2438  5131.4 2445.75
  5143.3 2449.54  5173.9 2455.14  5183.5 2455.94  5188.6 2457.39  5214.6 2459.08
#Mann= 5 ,-1 , 0
  4748.3     .07       0  4944.4     .16       0  4964.5     .07       0
  4980.2     .16       0  5076.6     .07       0
Bank Sta=4964.5,4980.2
XS Rating Curve= 0 ,0
Exp/Cntr=0.3,0.1

Type RM Length L Ch R = 1 ,42069   ,498,498,498
BEGIN DESCRIPTION:
Holder Creek 69.0
END DESCRIPTION:
XS GIS Cut Line= 3
      1403805.01      6805537.99      1403956.65      6805384.03
        1404105.      6805137.99
#Sta/Elev= 30
  4783.9 2462.48  4819.2  2459.8  4833.4 2457.69  4854.6 2453.51  4868.7 2449.17
    4890 2445.17  4904.1 2441.44  4911.1 2438.66  4918.2 2434.45  4925.3 2428.79
  4939.4 2427.68  4960.7 2429.54  4967.7 2429.49  4995.3 2424.73    5000 2424.73
  5001.8 2421.29  5002.3 2420.79  5017.1 2420.79  5017.6 2421.29  5018.7 2422.39
    5031 2427.75  5130.6 2430.63  5193.9 2433.26  5215.5    2435  5228.9 2438.09
  5258.2 2448.93  5268.2 2451.47  5279.5 2453.89  5284.4 2455.97  5287.3 2455.97
#Mann= 5 ,-1 , 0
  4783.9     .07       0  5001.8     .07       0  5017.6     .07       0
  5130.6     .16       0  5268.2     .07       0
Bank Sta=5001.8,5017.6
XS Rating Curve= 0 ,0
Exp/Cntr=0.3,0.1

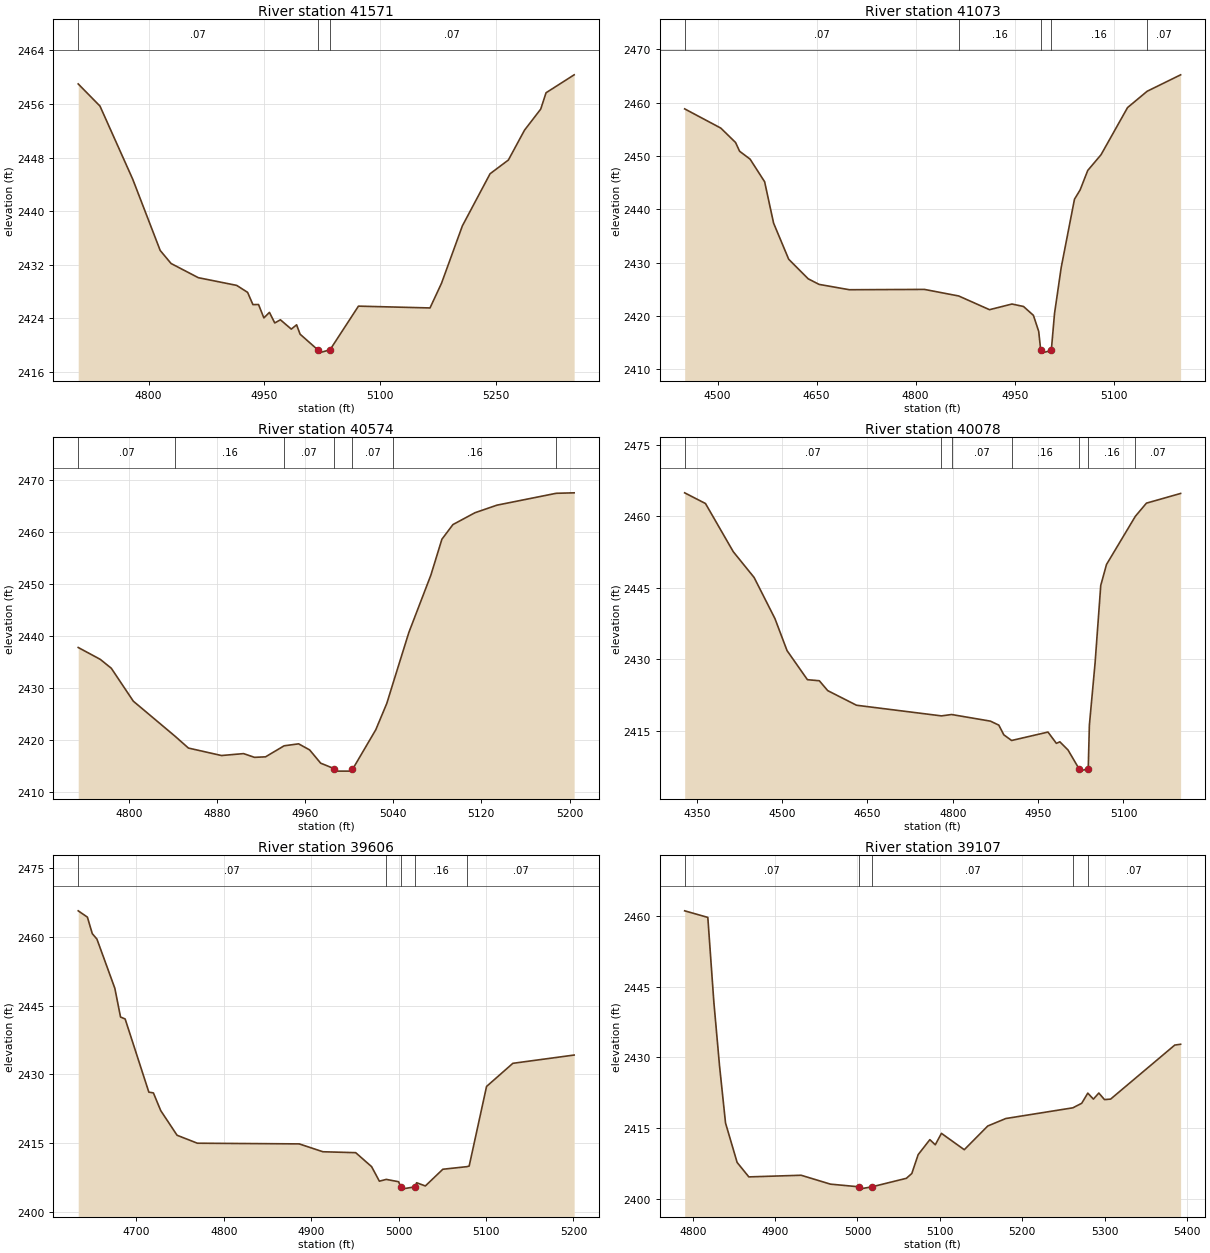
Type RM Length L Ch R = 1 ,41571   ,498,498,498
BEGIN DESCRIPTION:
Holder Creek 68.0
END DESCRIPTION:
XS GIS Cut Line= 3
      1404154.97      6805838.03      1404365.48      6805636.83
      1404654.99      6805438.01
#Sta/Elev= 30
  4708.8    2459    4737 2455.69  4779.4 2444.77    4815 2434.12  4829.1 2432.17
  4864.4 2430.05  4914.1  2428.9  4928.2 2427.86  4935.1 2426.03  4942.4 2426.04
  4949.3 2424.04  4956.5 2424.87  4963.4 2423.29  4970.7 2423.76  4984.8 2422.37
  4991.7 2423.01  4996.2 2421.61  5019.1 2419.28  5019.6 2418.78    5035 2419.28
  5071.8  2425.8  5164.5 2425.53  5179.4 2429.22  5206.4 2437.79  5242.3 2445.58
    5266 2447.63  5286.9 2452.09  5307.9 2455.24  5314.8 2457.68  5351.2 2460.36
#Mann= 3 ,-1 , 0
  4708.8     .07       0  5019.1     .07       0    5035     .07       0
Bank Sta=5019.1,5035
XS Rating Curve= 0 ,0
Exp/Cntr=0.3,0.1

Type RM Length L Ch R = 1 ,41073   ,499,499,499
BEGIN DESCRIPTION:
Holder Creek 67.0
END DESCRIPTION:
XS GIS Cut Line= 3
      1404304.97      6806038.01       1404804.6      6805808.33
      1405004.98        6805788.
#Sta/Elev= 30
  4450.1 2458.83  4504.8 2455.23  4527.2 2452.53  4533.3 2450.89  4549.2 2449.41
  4571.2 2445.18  4584.8 2437.42  4607.7 2430.65  4637.2 2426.99  4653.7 2425.94
  4699.6 2424.94  4813.3    2425  4865.2 2423.77  4911.9  2421.2  4945.9 2422.26
  4963.4  2421.8  4978.4 2420.14  4986.4 2417.14  4989.5 2413.56    4990 2413.06
  5005.5 2413.56  5010.4  2420.5  5020.5 2429.11  5040.6  2441.9  5049.2 2443.65
  5060.7 2447.29  5080.8 2450.23    5121 2459.07  5150.7 2462.13  5201.4 2465.21
#Mann= 5 ,-1 , 0
  4450.1     .07       0  4865.2     .16       0  4989.5     .07       0
  5005.5     .16       0  5150.7     .07       0
Bank Sta=4989.5,5005.5
XS Rating Curve= 0 ,0
Exp/Cntr=0.3,0.1

Type RM Length L Ch R = 1 ,40574   ,496,496,496
BEGIN DESCRIPTION:
Holder Creek 66.0
END DESCRIPTION:
XS GIS Cut Line= 3
      1404755.02        6806238.      1405000.81      6806239.73
      1405205.01        6806238.
#Sta/Elev= 30
  4754.2  2437.8  4774.2 2435.52  4784.2 2433.81  4804.2 2427.47    4842 2420.74
  4854.2 2418.45  4884.2 2417.01  4904.2 2417.38  4914.2 2416.66  4924.2 2416.76
    4941 2418.88  4954.2 2419.26  4964.2 2418.09  4974.2 2415.54  4986.2 2414.51
  4986.7 2414.01  5001.7 2414.01  5002.2 2414.51  5004.6 2414.89  5024.2 2421.97
  5034.2 2427.04    5040 2431.02  5054.2 2440.68  5074.2 2451.73  5084.2 2458.63
  5094.2 2461.45  5114.2 2463.73  5134.2 2465.19  5187.9 2467.47  5204.2 2467.56
#Mann= 7 ,-1 , 0
  4754.2     .07       0    4842     .16       0    4941     .07       0
  4986.2     .07       0  5002.2     .07       0    5040     .16       0
  5187.9     .07       0
Bank Sta=4986.2,5002.2
XS Rating Curve= 0 ,0
Exp/Cntr=0.3,0.1

Type RM Length L Ch R = 1 ,40078   ,472,472,472
BEGIN DESCRIPTION:
Holder Creek 65.0
END DESCRIPTION:
XS GIS Cut Line= 3
        1404555.        6807088.      1405105.04      6806702.98
      1405304.98        6806688.
#Sta/Elev= 30
  4328.6 2464.96  4365.2 2462.71    4414 2452.59  4450.7 2447.16  4487.3 2438.52
  4508.6 2431.79  4544.4 2425.68  4565.3 2425.46  4580.1 2423.38  4630.7 2420.31
  4780.1 2418.07  4797.8 2418.36  4866.1 2416.97  4880.9 2416.13  4889.7 2414.09
  4903.4  2412.9  4967.3 2414.67  4982.1  2412.3  4988.2 2412.62  5002.5 2410.91
  5021.9 2406.96  5022.4 2406.46  5038.1 2406.96  5040.1 2416.12  5050.1 2429.16
  5060.1  2445.5  5070.2  2449.9    5121 2460.04  5140.4 2462.79  5200.5 2464.83
#Mann= 7 ,-1 , 0
  4328.6     .07       0  4780.1     .16       0  4797.8     .07       0
  4903.4     .16       0  5021.9     .07       0  5038.1     .16       0
    5121     .07       0
Bank Sta=5021.9,5038.1
XS Rating Curve= 0 ,0
Exp/Cntr=0.3,0.1

Type RM Length L Ch R = 1 ,39606   ,499,499,499
BEGIN DESCRIPTION:
Holder Creek 64.0
END DESCRIPTION:
XS GIS Cut Line= 3
      1404655.02        6807238.      1405004.45      6807127.46
      1405204.97        6807138.
#Sta/Elev= 30
  4633.5 2465.63    4644 2464.26  4649.6 2460.66  4654.9 2459.48  4675.4 2448.76
  4681.9 2442.51  4687.2 2442.07  4714.3 2426.14  4719.5 2425.98  4727.9 2422.12
  4746.6 2416.75  4769.8 2415.02  4886.3 2414.87  4913.4 2413.16  4950.9 2412.96
  4969.1 2409.92    4978 2406.75  4985.9 2407.14    5000 2406.63  5002.4 2405.52
  5002.9 2405.02  5018.7 2405.52  5020.6 2406.41  5030.6 2405.71  5050.6 2409.35
    5078 2409.91  5080.7 2410.04  5100.6 2427.38  5130.7 2432.42  5200.8 2434.22
#Mann= 5 ,-1 , 0
  4633.5     .07       0  4985.9     .16       0  5002.4     .07       0
  5018.7     .16       0    5078     .07       0
Bank Sta=5002.4,5018.7
XS Rating Curve= 0 ,0
Exp/Cntr=0.3,0.1

Type RM Length L Ch R = 1 ,39107   ,496,496,496
BEGIN DESCRIPTION:
Holder Creek 63.0
END DESCRIPTION:
XS GIS Cut Line= 3
        1404755.        6807738.       1404907.7      6807594.12
      1405204.99      6807338.01
#Sta/Elev= 30
  4790.2 2461.17  4818.3 2459.77  4825.6 2441.83  4832.5 2428.27  4839.8 2416.06
  4853.9 2407.67  4868.1  2404.6  4931.6 2404.95  4967.2 2403.06  5001.4  2402.5
  5001.9    2402  5017.8  2402.5  5059.4  2404.3    5066 2405.32  5073.7 2409.33
  5087.9 2412.52  5094.5 2411.43    5102 2413.86  5129.7 2410.38  5158.2 2415.42
  5180.1 2417.01  5261.6 2419.29  5272.3 2420.25  5279.7 2422.41  5286.5 2421.14
  5293.1 2422.43    5300 2421.03  5307.4 2421.14  5385.3 2432.63  5392.4  2432.8
#Mann= 5 ,-1 , 0
  4790.2     .07       0  5001.4     .07       0  5017.8     .07       0
  5261.6     .16       0  5279.7     .07       0
Bank Sta=5001.4,5017.8
XS Rating Curve= 0 ,0
Exp/Cntr=0.3,0.1

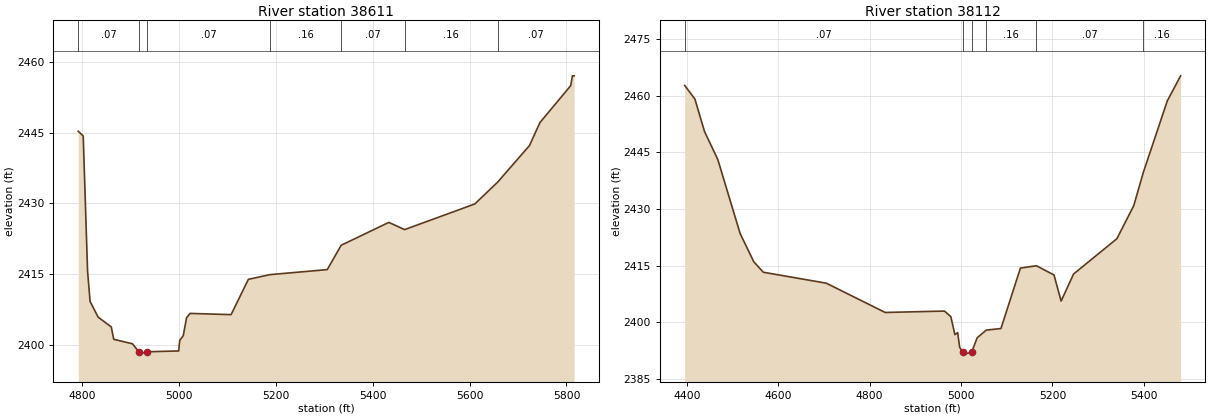
Type RM Length L Ch R = 1 ,38611   ,499,499,499
BEGIN DESCRIPTION:
Holder Creek 62.0
END DESCRIPTION:
XS GIS Cut Line= 3
      1404954.98        6807888.      1405157.45      6807843.48
      1405755.03      6807287.97
#Sta/Elev= 30
  4792.7 2445.29    4803  2444.3    4812 2415.66  4817.2 2409.22  4833.7  2405.9
  4860.9 2403.82    4866 2401.19  4904.7 2400.24  4917.6 2398.55  4918.1 2398.05
    4934 2398.55    5000 2398.72  5002.1 2400.96  5009.4 2401.96  5016.3 2405.78
  5023.6 2406.68  5108.1 2406.42  5143.8  2413.9  5188.5  2414.9  5306.5 2415.96
  5335.2 2421.12  5433.6 2425.97  5466.1 2424.44  5610.9 2429.87  5657.8 2434.47
  5723.8 2442.26  5745.3 2447.12  5808.8 2454.95  5812.4 2457.03  5815.9 2457.03
#Mann= 7 ,-1 , 0
  4792.7     .07       0  4917.6     .07       0    4934     .07       0
  5188.5     .16       0  5335.2     .07       0  5466.1     .16       0
  5657.8     .07       0
Bank Sta=4917.6,4934
XS Rating Curve= 0 ,0
Exp/Cntr=0.3,0.1

Type RM Length L Ch R = 1 ,38112   ,464,464,464
BEGIN DESCRIPTION:
Holder Creek 61.0
END DESCRIPTION:
XS GIS Cut Line= 3
      1405205.02      6808587.97      1405544.96      6808088.11
        1405955.        6807838.
#Sta/Elev= 30
  4395.5 2462.73  4417.9 2459.11  4438.9 2450.52    4468 2443.08  4516.8 2423.48
  4546.6 2416.01  4567.6 2413.22  4705.3 2410.32    4834 2402.56  4963.9 2402.93
  4977.7 2401.44  4986.6 2396.68  4992.6 2397.21    4997 2393.32  5004.2 2392.02
  5004.7 2391.52  5023.3 2392.02  5035.2 2395.84  5055.3 2397.89  5087.3  2398.3
  5129.9 2414.32  5164.9 2414.94  5203.4 2412.49  5218.9 2405.57  5246.1 2412.74
  5340.9 2422.11  5377.7 2430.83  5398.9 2439.74  5451.3 2458.67  5480.3 2465.27
#Mann= 6 ,-1 , 0
  4395.5     .07       0  5004.2     .07       0  5023.3     .07       0
  5055.3     .16       0  5164.9     .07       0  5398.9     .16       0
Bank Sta=5004.2,5023.3
XS Rating Curve= 0 ,0
Exp/Cntr=0.3,0.1