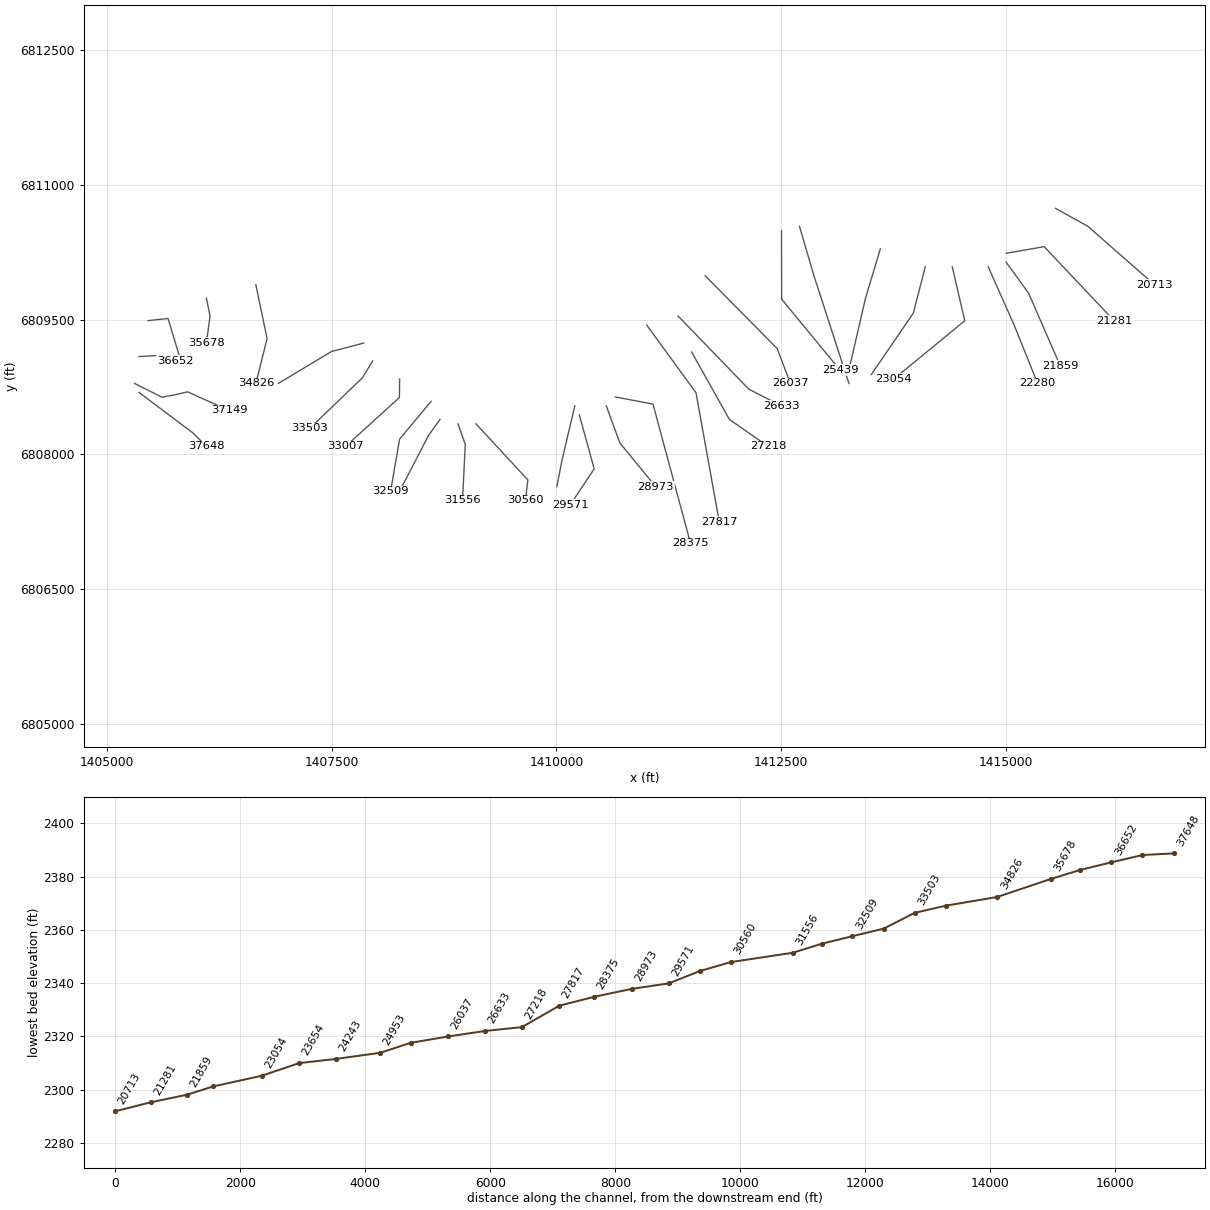
HEC-RAS study Holder Creek.prj: Holder Creek Base Level Engineering

--- Holder Creek.g01 (geometry) --- (continued)

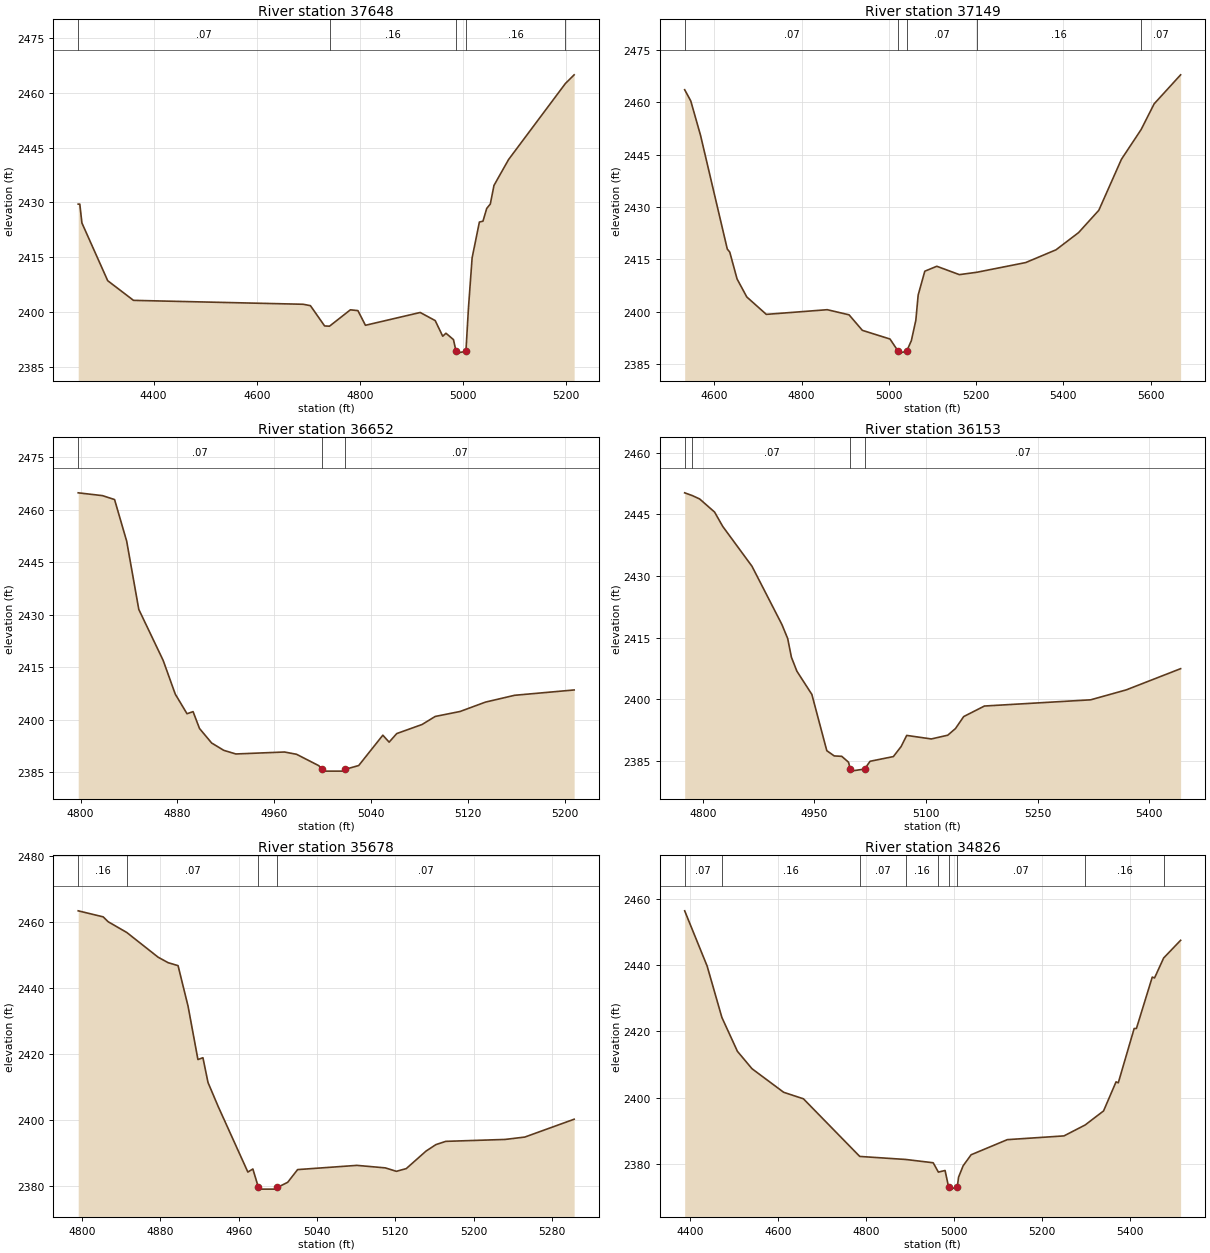
Type RM Length L Ch R = 1 ,37648   ,499,499,499
BEGIN DESCRIPTION:
Holder Creek 60.0
END DESCRIPTION:
XS GIS Cut Line= 3
      1405355.04      6808687.97      1405951.55      6808239.49
      1406104.98      6808088.02
#Sta/Elev= 30
  4253.7 2429.53  4256.8 2429.53  4260.9 2424.37  4310.9 2408.55  4360.9 2403.16
    4690 2402.09  4704.1 2401.71  4731.6 2396.15  4741.1 2396.08  4781.6 2400.57
  4796.2 2400.35  4810.8 2396.33    4917 2399.84  4946.1 2397.62  4960.7 2393.33
    4967 2394.15  4981.5 2392.41  4986.6  2389.2  4987.1  2388.7  5005.7  2389.2
  5010.6 2401.05  5017.7 2414.81  5031.8 2424.62  5038.8 2424.87    5046 2428.35
    5053 2429.57  5060.1 2434.66  5088.4 2441.75  5198.5 2462.57  5215.6 2464.97
#Mann= 5 ,-1 , 0
  4253.7     .07       0  4741.1     .16       0  4986.6     .07       0
  5005.7     .16       0  5198.5     .07       0
Bank Sta=4986.6,5005.7
XS Rating Curve= 0 ,0
Exp/Cntr=0.3,0.1

Type RM Length L Ch R = 1 ,37149   ,497,497,497
BEGIN DESCRIPTION:
Holder Creek 59.0
END DESCRIPTION:
XS GIS Cut Line= 5
      1405305.02      6808787.99      1405610.63      6808634.85
      1405734.69      6808657.87      1405894.48      6808694.75
        1406355.        6808488.
#Sta/Elev= 30
    4532 2463.61  4545.9 2460.42  4568.3 2450.56  4629.7 2417.93  4635.3 2417.08
  4652.1 2409.36  4674.4  2404.2  4719.1 2399.21  4858.8 2400.55  4908.8 2399.08
  4939.3 2394.63  5002.7 2392.14  5021.6  2388.6  5022.1  2388.1  5040.7  2388.6
  5051.6 2391.68  5061.9 2397.55  5067.2 2404.75  5082.4 2411.58  5109.9    2413
  5161.7  2410.6  5201.7 2411.28  5313.7 2414.06  5383.2 2417.72    5435 2422.66
  5481.3 2429.05  5533.1 2443.66  5578.4 2452.22  5608.1 2459.56  5668.8 2467.88
#Mann= 5 ,-1 , 0
    4532     .07       0  5021.6     .07       0  5040.7     .07       0
  5201.7     .16       0  5578.4     .07       0
Bank Sta=5021.6,5040.7
XS Rating Curve= 0 ,0
Exp/Cntr=0.3,0.1

Type RM Length L Ch R = 1 ,36652   ,499,499,499
BEGIN DESCRIPTION:
Holder Creek 58.0
END DESCRIPTION:
XS GIS Cut Line= 3
      1405355.03        6809088.      1405556.65      6809098.68
      1405754.98      6809038.01
#Sta/Elev= 30
  4798.1 2464.84  4818.1 2464.04  4828.1 2462.92  4838.1 2451.03  4848.1 2431.55
  4868.2 2416.99  4878.2 2407.36  4887.9 2401.75  4892.9 2402.35  4898.2 2397.54
  4908.2  2393.4  4918.2  2391.3  4928.2 2390.26  4968.3 2390.82  4978.3 2390.17
  4996.7 2386.91  4999.2 2385.86  4999.7 2385.36  5017.8 2385.36  5018.3 2385.86
  5029.6 2386.96  5049.5 2395.62  5054.7 2393.64    5061 2396.09  5081.9 2398.68
  5092.7 2400.97  5113.3  2402.4  5134.2 2405.07  5158.3 2407.02  5207.4 2408.54
#Mann= 3 ,-1 , 0
  4798.1     .07       0  4999.2     .07       0  5018.3     .07       0
Bank Sta=4999.2,5018.3
XS Rating Curve= 0 ,0
Exp/Cntr=0.3,0.1

Type RM Length L Ch R = 1 ,36153   ,475,475,475
BEGIN DESCRIPTION:
Holder Creek 57.0
END DESCRIPTION:
XS GIS Cut Line= 3
        1405455.        6809488.      1405678.13      6809511.83
        1405805.      6809088.02
#Sta/Elev= 30
  4775.6 2450.22  4786.1 2449.53  4795.7 2448.73  4815.8 2445.54  4826.8 2442.04
  4866.1 2432.35  4906.3 2418.19  4914.1 2414.77  4919.1 2410.22  4926.5 2406.81
  4946.6 2401.17  4966.7 2387.47  4976.7  2386.2  4986.8  2386.1  4995.9 2384.67
  4998.3    2383  4998.8  2382.5  5017.4    2383  5024.9  2384.9  5056.2 2386.04
  5066.6 2388.48  5074.1 2391.19  5107.2 2390.33  5129.3 2391.24  5139.7 2392.86
  5150.7 2395.77  5178.6 2398.34  5321.4 2399.85  5369.3 2402.27  5442.4 2407.43
#Mann= 4 ,-1 , 0
  4775.6     .16       0  4786.1     .07       0  4998.3     .07       0
  5017.4     .07       0
Bank Sta=4998.3,5017.4
XS Rating Curve= 0 ,0
Exp/Cntr=0.3,0.1

Type RM Length L Ch R = 1 ,35678   ,852,852,852
BEGIN DESCRIPTION:
Holder Creek 56.0
END DESCRIPTION:
XS GIS Cut Line= 3
        1406105.      6809737.99      1406145.02      6809538.05
        1406105.      6809238.01
#Sta/Elev= 30
  4796.1 2463.44  4821.6 2461.61  4826.7 2460.13  4845.7 2456.88  4877.7 2449.39
  4887.9 2447.73  4898.1 2446.82  4908.3 2434.54  4918.4 2418.36  4923.5 2418.91
  4928.7  2411.4  4938.9 2404.25  4969.4 2384.25  4974.5 2385.19  4980.2 2379.58
  4980.7 2379.08    4999 2379.08  4999.5 2379.58  5010.1 2381.15  5020.2    2385
  5080.8 2386.28  5109.8 2385.52  5121.1 2384.48  5131.2  2385.3  5151.4 2390.61
  5161.5 2392.58  5171.6 2393.56  5232.1 2394.14  5252.3 2394.86  5302.7 2400.27
#Mann= 4 ,-1 , 0
  4796.1     .16       0  4845.7     .07       0  4980.2     .07       0
  4999.5     .07       0
Bank Sta=4980.2,4999.5
XS Rating Curve= 0 ,0
Exp/Cntr=0.3,0.1

Type RM Length L Ch R = 1 ,34826   ,827,827,827
BEGIN DESCRIPTION:
Holder Creek 54.0
END DESCRIPTION:
XS GIS Cut Line= 3
        1406655.      6809887.99      1406780.01      6809287.97
      1406654.99      6808787.97
#Sta/Elev= 30
  4387.1 2456.38  4438.2  2439.7  4471.8 2424.17  4507.1 2413.96  4540.3  2408.7
  4612.3 2401.59  4657.3 2399.62  4785.4 2382.22  4890.4  2381.3  4952.5 2380.31
  4964.3 2377.49  4979.5 2377.98  4987.8 2372.85  4988.3 2372.35  5007.1 2372.85
  5010.3 2375.99  5020.6 2379.39  5038.7 2382.72  5121.1 2387.29    5250 2388.42
  5298.1 2391.71  5340.1 2395.96  5368.5 2404.74  5373.6 2404.45  5409.7 2420.84
  5414.9 2420.87  5450.9 2436.37  5456.1 2436.12  5476.8 2442.14  5515.4 2447.48
#Mann= 9 ,-1 , 0
  4387.1     .07       0  4471.8     .16       0  4785.4     .07       0
  4890.4     .16       0  4964.3     .07       0  4987.8     .07       0
  5007.1     .07       0  5298.1     .16       0  5476.8     .07       0
Bank Sta=4987.8,5007.1
XS Rating Curve= 0 ,0
Exp/Cntr=0.3,0.1

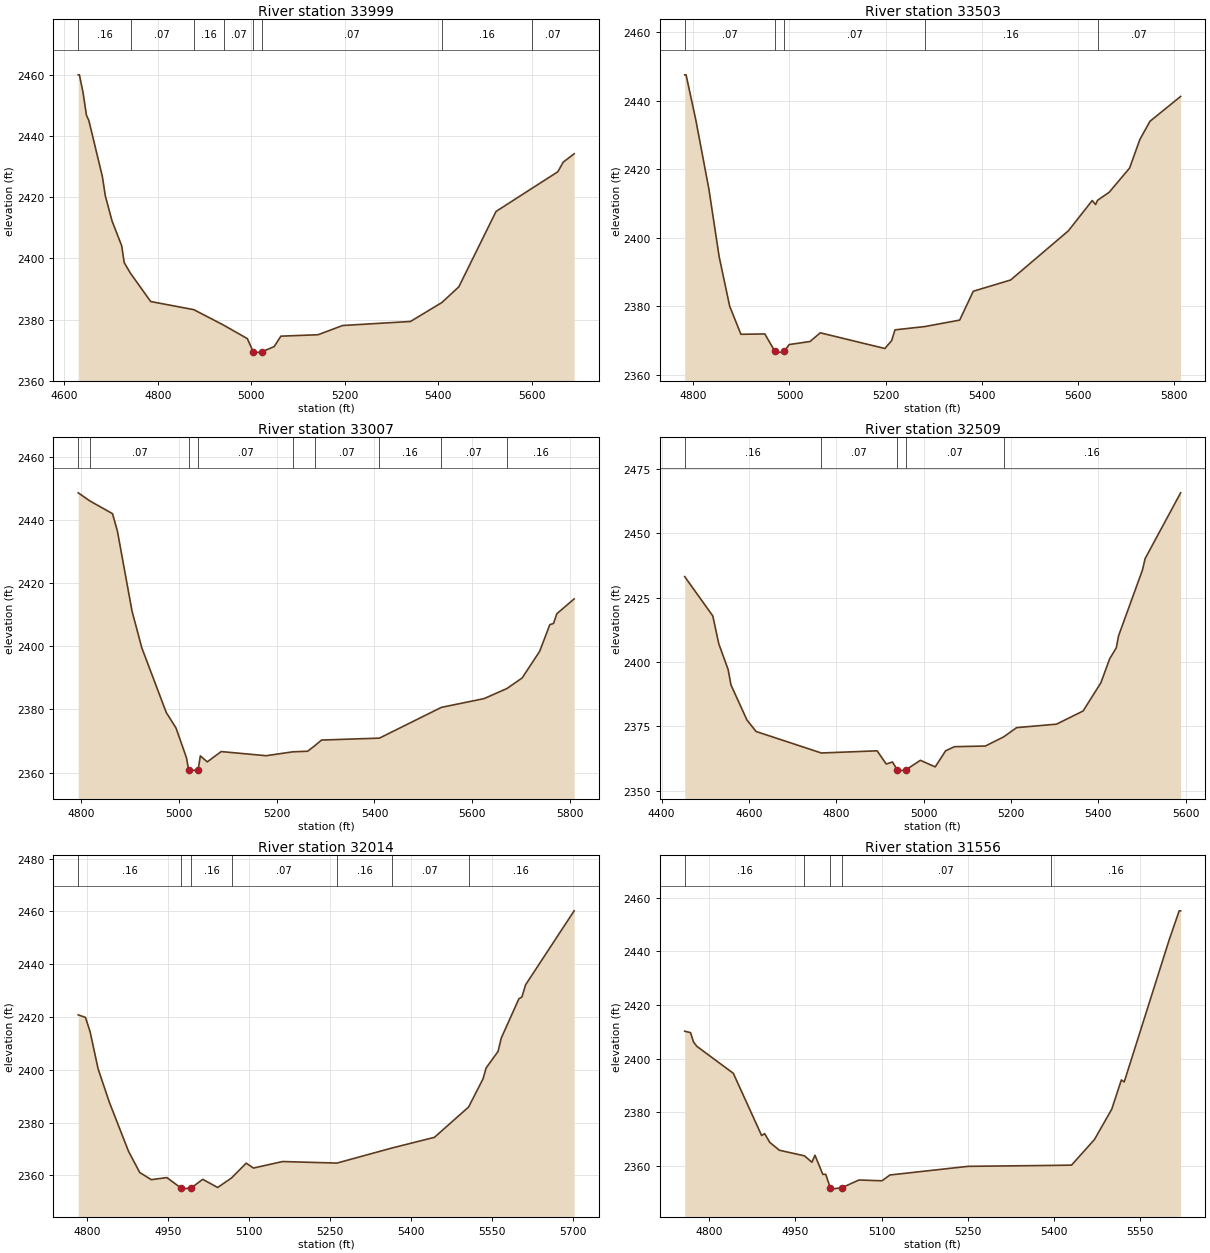
Type RM Length L Ch R = 1 ,33999   ,496,496,496
BEGIN DESCRIPTION:
Holder Creek 52.0
END DESCRIPTION:
XS GIS Cut Line= 3
        1407855.        6809238.      1407496.82      6809144.04
      1406904.97      6808787.98
#Sta/Elev= 30
  4629.7 2459.96  4632.3 2459.96    4640 2454.21  4647.3 2446.77  4652.5 2445.03
  4681.4 2426.73  4687.7 2420.45  4702.1 2412.24  4722.8 2404.08  4728.1 2398.63
  4741.9 2395.06  4784.8 2385.92    4877 2383.27  4940.7 2378.22  4991.5 2373.81
    5004 2369.57  5004.5 2369.07  5023.6 2369.57  5048.8 2371.19  5063.3 2374.61
  5142.9 2375.08  5195.3 2378.09  5340.6 2379.41  5407.9 2385.62    5444 2390.73
  5523.6 2415.34    5601 2422.94  5655.7 2428.29  5667.4 2431.46  5690.7 2434.17
#Mann= 8 ,-1 , 0
  4629.7     .16       0  4741.9     .07       0    4877     .16       0
  4940.7     .07       0    5004     .07       0  5023.6     .07       0
  5407.9     .16       0    5601     .07       0
Bank Sta=5004,5023.6
XS Rating Curve= 0 ,0
Exp/Cntr=0.3,0.1

Type RM Length L Ch R = 1 ,33503   ,496,496,496
BEGIN DESCRIPTION:
Holder Creek 51.0
END DESCRIPTION:
XS GIS Cut Line= 3
      1407954.99      6809037.98       1407841.8      6808851.66
      1407254.97      6808287.98
#Sta/Elev= 30
    4782 2447.61  4784.9 2447.61  4805.2 2434.42  4832.4 2414.26  4853.7 2394.56
  4875.6 2380.09    4899 2371.89  4948.7 2371.99  4969.8 2366.89  4970.3 2366.39
  4989.4 2366.89  4999.2 2368.89  5042.7 2369.78  5064.1 2372.32  5198.4 2367.74
  5212.5 2370.02  5219.5 2373.18  5281.7 2374.15  5354.1 2376.03  5382.4 2384.45
    5460 2387.73  5580.2 2402.08  5629.8 2410.93  5636.8 2409.75  5640.8 2410.98
  5665.1 2413.34  5707.5 2420.39  5728.9 2428.73    5750 2434.06  5813.7  2441.3
#Mann= 5 ,-1 , 0
    4782     .07       0  4969.8     .07       0  4989.4     .07       0
  5281.7     .16       0  5640.8     .07       0
Bank Sta=4969.8,4989.4
XS Rating Curve= 0 ,0
Exp/Cntr=0.3,0.1

Type RM Length L Ch R = 1 ,33007   ,498,498,498
BEGIN DESCRIPTION:
Holder Creek 50.0
END DESCRIPTION:
XS GIS Cut Line= 3
        1408255.      6808838.05      1408252.95      6808632.16
      1407654.99      6808087.99
#Sta/Elev= 30
  4794.1 2448.55  4818.5 2445.93  4864.2 2441.96  4874.2 2436.51  4904.2  2411.1
  4924.2 2399.48  4974.2 2379.02  4994.2  2374.1  5015.6 2364.66  5019.9 2360.96
  5020.4 2360.46  5039.5 2360.96  5043.9 2365.28  5058.1 2363.39  5086.5 2366.65
  5178.4 2365.34  5232.9 2366.57  5263.5 2366.76  5277.5 2368.45  5291.9  2370.3
  5410.1  2370.9  5536.9 2380.64  5624.4 2383.42    5671 2386.61  5702.1 2389.95
  5737.9 2398.36  5758.8 2406.84  5766.3 2407.19    5773 2410.27  5808.5 2414.97
#Mann= 9 ,-1 , 0
  4794.1     .16       0  4818.5     .07       0  5019.9     .07       0
  5039.5     .07       0  5232.9     .16       0  5277.5     .07       0
  5410.1     .16       0  5536.9     .07       0    5671     .16       0
Bank Sta=5019.9,5039.5
XS Rating Curve= 0 ,0
Exp/Cntr=0.3,0.1

Type RM Length L Ch R = 1 ,32509   ,495,495,495
BEGIN DESCRIPTION:
Holder Creek 49.0
END DESCRIPTION:
XS GIS Cut Line= 3
      1408604.97      6808587.96      1408254.71      6808167.81
        1408155.      6807588.02
#Sta/Elev= 30
    4453 2433.23  4517.4 2417.94  4531.1 2407.12  4552.5 2397.11    4559 2391.13
  4595.5 2377.53  4616.3 2373.06  4765.8  2364.7  4893.6 2365.54  4914.4 2360.42
  4928.7  2361.2  4939.6 2358.15  4940.1 2357.65  4959.5 2358.15  4992.5 2361.85
  5026.5  2359.3  5050.5 2365.57  5070.8 2367.15  5141.3  2367.4  5183.3 2370.97
  5212.9 2374.55  5304.2  2375.9  5365.1 2381.02  5405.7 2391.95    5426 2401.34
    5441 2405.52  5446.3 2410.25  5500.9 2435.74  5507.1 2440.23  5588.3 2465.77
#Mann= 5 ,-1 , 0
    4453     .16       0  4765.8     .07       0  4939.6     .07       0
  4959.5     .07       0  5183.3     .16       0
Bank Sta=4939.6,4959.5
XS Rating Curve= 0 ,0
Exp/Cntr=0.3,0.1

Type RM Length L Ch R = 1 ,32014   ,458,458,458
BEGIN DESCRIPTION:
Holder Creek 48.0
END DESCRIPTION:
XS GIS Cut Line= 3
        1408705.        6808388.      1408578.07      6808211.87
      1408254.98      6807587.96
#Sta/Elev= 30
  4782.9 2420.79  4796.4 2419.82    4805 2414.36  4819.7 2400.42  4840.6 2387.72
  4876.2 2369.13    4897 2361.07  4918.5 2358.36  4947.3 2359.16    4973 2355.28
  4973.5 2354.78  4992.9 2355.28  5013.8  2358.5  5041.5  2355.4  5067.3 2359.03
  5094.4 2364.62  5107.9 2362.77    5162 2365.23  5262.8 2364.65  5364.6 2370.35
  5443.5  2374.4  5506.8 2385.87  5533.6 2396.54  5539.4 2400.69  5561.5 2406.95
  5567.4 2411.99  5600.1 2426.87  5605.8 2427.59  5612.5 2432.17  5702.6  2460.2
#Mann= 7 ,-1 , 0
  4782.9     .16       0    4973     .07       0  4992.9     .16       0
  5067.3     .07       0  5262.8     .16       0  5364.6     .07       0
  5506.8     .16       0
Bank Sta=4973,4992.9
XS Rating Curve= 0 ,0
Exp/Cntr=0.3,0.1

Type RM Length L Ch R = 1 ,31556   ,996,996,996
BEGIN DESCRIPTION:
Holder Creek 47.0
END DESCRIPTION:
XS GIS Cut Line= 3
        1408905.        6808338.      1408985.59      6808108.64
        1408955.        6807488.
#Sta/Elev= 30
  4756.9 2410.26  4767.1 2409.75  4772.4 2406.22  4778.1 2404.64  4841.7 2394.59
    4891 2371.42  4896.3  2372.1  4905.3 2368.83    4922 2365.92  4965.7 2363.84
  4978.7 2361.44    4984 2364.07  4997.7 2356.94  5002.8 2356.94  5010.7 2351.93
  5011.2 2351.43  5030.6 2351.93  5060.7 2354.83  5100.8 2354.54  5114.7  2356.7
  5250.9 2359.92  5395.3 2360.26  5431.2 2360.37  5471.2 2369.91  5501.3 2381.19
  5518.1 2392.12  5523.1 2391.37  5601.4 2444.26  5618.9 2455.12  5621.4 2455.12
#Mann= 5 ,-1 , 0
  4756.9     .16       0  4965.7     .07       0  5010.7     .07       0
  5030.6     .07       0  5395.3     .16       0
Bank Sta=5010.7,5030.6
XS Rating Curve= 0 ,0
Exp/Cntr=0.3,0.1

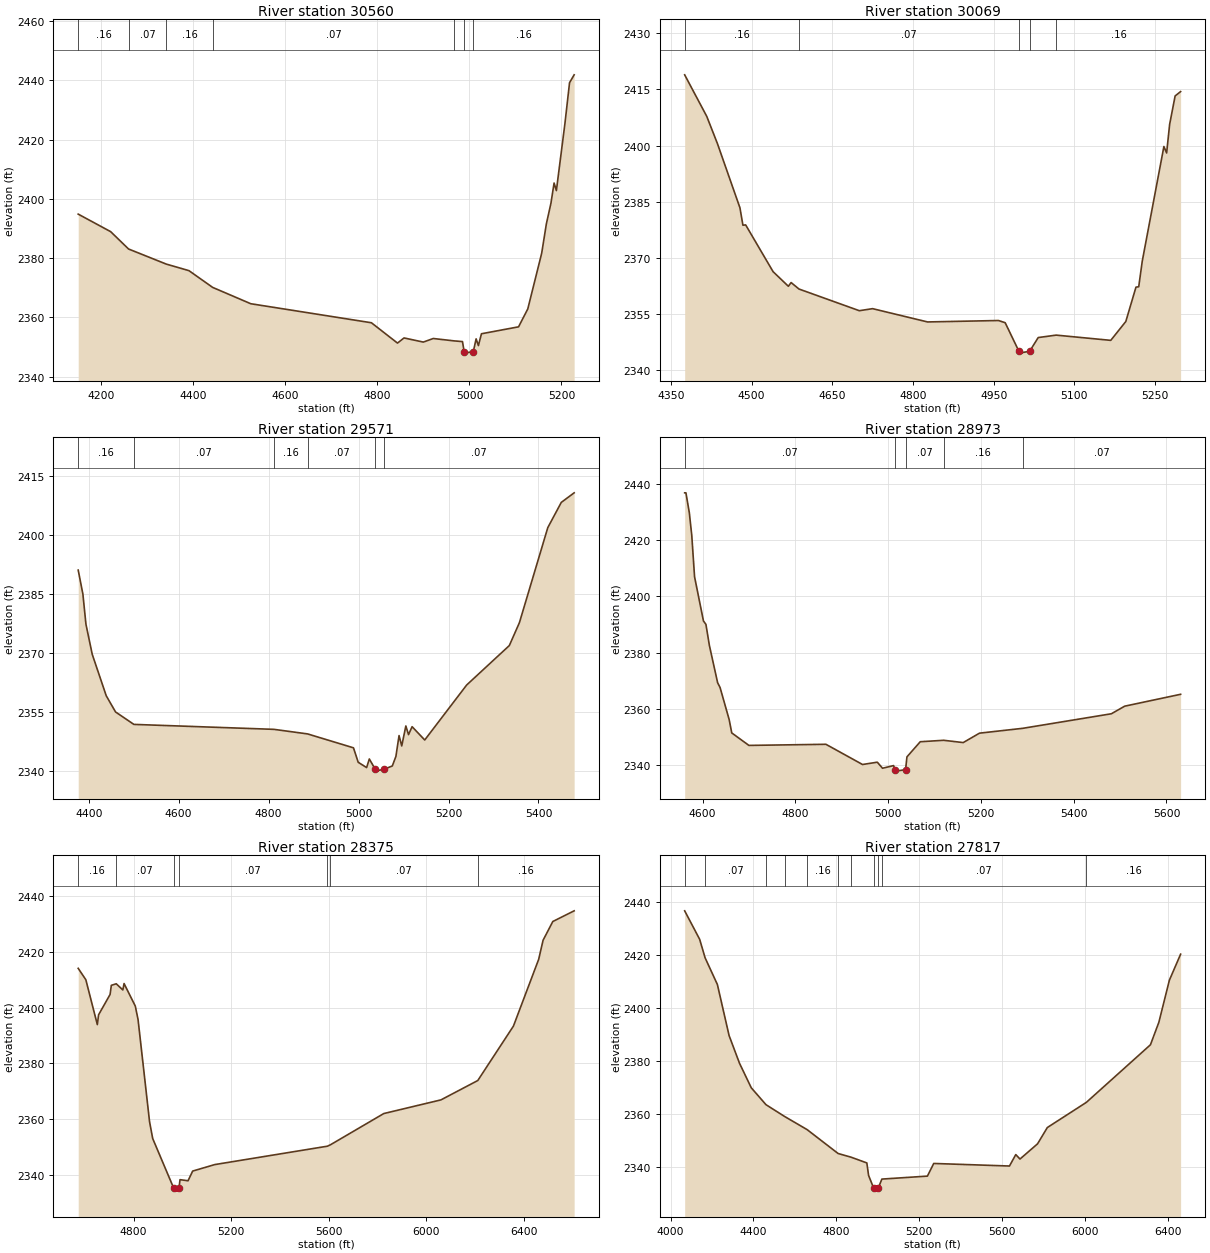
Type RM Length L Ch R = 1 ,30560   ,491,491,491
BEGIN DESCRIPTION:
Holder Creek 46.0
END DESCRIPTION:
XS GIS Cut Line= 3
      1409105.03      6808337.97      1409682.14      6807713.91
        1409655.      6807488.03
#Sta/Elev= 30
    4150 2394.86  4220.5 2388.94  4259.4 2383.08  4341.2 2377.99  4390.6 2375.77
  4442.1 2370.11    4525 2364.59    4787 2358.17  4843.7  2351.3  4857.9 2353.04
  4899.8 2351.64  4921.4 2352.85    4967 2352.04  4984.9 2351.81  4988.5 2348.41
    4989 2347.91  5008.4 2348.41  5014.5 2352.73  5019.5 2350.46  5026.1 2354.45
  5106.7 2356.79  5126.8 2362.85    5157 2381.68  5167.1 2391.54  5177.2 2398.64
  5183.9 2405.37  5188.9 2402.82  5207.4 2425.37  5217.5 2439.25  5227.5 2441.91
#Mann= 7 ,-1 , 0
    4150     .16       0  4259.4     .07       0  4341.2     .16       0
  4442.1     .07       0    4967     .16       0  4988.5     .07       0
  5008.4     .16       0
Bank Sta=4988.5,5008.4
XS Rating Curve= 0 ,0
Exp/Cntr=0.3,0.1

Type RM Length L Ch R = 1 ,30069   ,498,498,498
BEGIN DESCRIPTION:
Holder Creek 45.0
END DESCRIPTION:
XS GIS Cut Line= 3
      1410205.01      6808538.02      1410061.21       6807930.2
      1410004.99      6807637.96
#Sta/Elev= 30
  4375.4 2418.91  4416.5  2407.8  4436.3 2400.54  4478.2 2383.37  4483.7 2378.74
  4488.8 2378.82  4539.8 2366.33  4568.2 2362.43  4573.3 2363.42    4588 2361.69
  4700.2  2355.9  4724.8 2356.45    4827  2352.9  4958.9 2353.28  4971.4 2352.69
  4996.9 2345.07  4997.4 2344.57  5016.9 2345.07  5032.8 2348.73  5066.2 2349.38
  5167.7 2347.98  5195.7 2353.02  5214.6  2362.2  5219.7  2362.3  5226.3 2369.16
  5266.5 2399.76  5271.6 2398.04  5277.2 2405.69  5287.4 2413.27  5297.6 2414.43
#Mann= 5 ,-1 , 0
  4375.4     .16       0    4588     .07       0  4996.9     .07       0
  5016.9     .07       0  5066.2     .16       0
Bank Sta=4996.9,5016.9
XS Rating Curve= 0 ,0
Exp/Cntr=0.3,0.1

Type RM Length L Ch R = 1 ,29571   ,598,598,598
BEGIN DESCRIPTION:
Holder Creek 44.0
END DESCRIPTION:
XS GIS Cut Line= 3
      1410254.99      6808438.04      1410420.43       6807837.1
        1410155.        6807438.
#Sta/Elev= 30
  4376.7 2391.01  4387.1 2384.93  4393.9 2377.26  4407.9 2369.61    4439  2359.1
  4459.7 2354.98  4500.5 2351.82    4812 2350.56  4886.7  2349.4  4988.7 2345.87
  4999.2  2342.2  5017.9 2340.85  5023.9 2343.04    5037 2340.45  5037.5 2339.95
    5057 2340.45    5075 2341.26    5083 2343.68    5090 2348.98    5096 2346.35
  5105.1 2351.42  5111.1 2349.22    5119 2351.24  5147.1 2347.86  5240.3 2361.82
  5335.2 2371.85  5357.6 2377.66  5420.7  2401.8  5450.7 2408.21  5479.3 2410.64
#Mann= 6 ,-1 , 0
  4376.7     .16       0  4500.5     .07       0    4812     .16       0
  4886.7     .07       0    5037     .07       0    5057     .07       0
Bank Sta=5037,5057
XS Rating Curve= 0 ,0
Exp/Cntr=0.3,0.1

Type RM Length L Ch R = 1 ,28973   ,598,598,598
BEGIN DESCRIPTION:
Holder Creek 43.0
END DESCRIPTION:
XS GIS Cut Line= 3
      1410554.99      6808538.02      1410705.81      6808126.06
      1411104.99      6807638.01
#Sta/Elev= 30
  4561.3 2436.87    4564 2436.87  4571.3 2429.81  4576.6 2421.72  4582.6    2407
  4601.8 2391.27  4607.1 2390.07  4614.6 2382.54  4632.3 2369.32  4637.6  2367.6
  4657.2 2356.19  4662.8 2351.43  4699.8 2346.99  4865.8 2347.39  4944.7  2340.2
  4976.6 2341.02  4987.8 2338.87  5011.7 2339.81  5014.8 2338.34  5015.3 2337.84
  5037.5 2338.34  5040.5 2342.92  5069.2  2348.3  5119.7 2348.81  5161.8    2348
  5196.9 2351.35    5290 2353.07  5481.2 2358.25  5509.9 2360.95  5630.5 2365.18
#Mann= 5 ,-1 , 0
  4561.3     .07       0  5014.8     .07       0  5037.5     .07       0
  5119.7     .16       0    5290     .07       0
Bank Sta=5014.8,5037.5
XS Rating Curve= 0 ,0
Exp/Cntr=0.3,0.1

Type RM Length L Ch R = 1 ,28375   ,558,558,558
BEGIN DESCRIPTION:
Holder Creek 42.0
END DESCRIPTION:
XS GIS Cut Line= 3
      1410654.96      6808638.01      1411074.87      6808558.31
      1411492.48      6807007.56
#Sta/Elev= 30
  4572.6 2414.06  4603.9 2409.97    4651 2393.89  4656.1 2397.39  4703.3  2404.7
  4708.4 2407.96  4728.6 2408.52  4755.6 2406.31  4760.6 2408.61  4806.7 2400.51
    4818 2395.69  4865.2 2359.02    4878 2353.04  4963.4 2335.39  4963.9 2334.89
  4986.1 2335.39    4990 2338.28    5023 2337.89  5041.8 2341.36  5132.4 2343.69
  5594.1 2350.28  5606.8 2350.79  5825.5 2361.99  6059.9 2366.89  6210.9 2373.83
    6357 2393.34  6460.6  2417.3  6478.6 2424.13  6518.5 2430.85    6606 2434.68
#Mann= 7 ,-1 , 0
  4572.6     .16       0  4728.6     .07       0  4963.4     .07       0
  4986.1     .07       0  5594.1     .16       0  5606.8     .07       0
  6210.9     .16       0
Bank Sta=4963.4,4986.1
XS Rating Curve= 0 ,0
Exp/Cntr=0.3,0.1

Type RM Length L Ch R = 1 ,27817   ,599,599,599
BEGIN DESCRIPTION:
Holder Creek 41.0
END DESCRIPTION:
XS GIS Cut Line= 3
      1411004.99      6809438.01      1411553.52      6808684.39
      1411812.64      6807244.52
#Sta/Elev= 30
  4067.9  2436.7  4140.2 2425.95  4166.5 2418.96  4225.9 2408.85  4282.3 2389.59
  4332.6 2379.12  4389.5 2369.83  4460.6 2363.45  4550.3    2359    4659 2354.04
  4808.9    2345  4871.1 2343.62  4947.6 2341.44  4956.1 2336.71    4980 2332.04
  4980.5 2331.54  5003.3 2332.04  5020.2 2335.33  5240.2 2336.46  5270.7 2341.24
  5636.5 2340.27  5666.9 2344.59  5687.3 2342.91  5772.1 2348.66  5819.3 2354.81
  6007.9 2364.33  6317.2 2386.08  6357.9 2394.58  6408.7 2410.48    6463 2420.32
#Mann= 11 ,-1 , 0
  4067.9     .16       0  4166.5     .07       0  4460.6     .16       0
  4550.3     .07       0    4659     .16       0  4808.9     .07       0
  4871.1     .16       0    4980     .07       0  5003.3     .16       0
  5020.2     .07       0  6007.9     .16       0
Bank Sta=4980,5003.3
XS Rating Curve= 0 ,0
Exp/Cntr=0.3,0.1

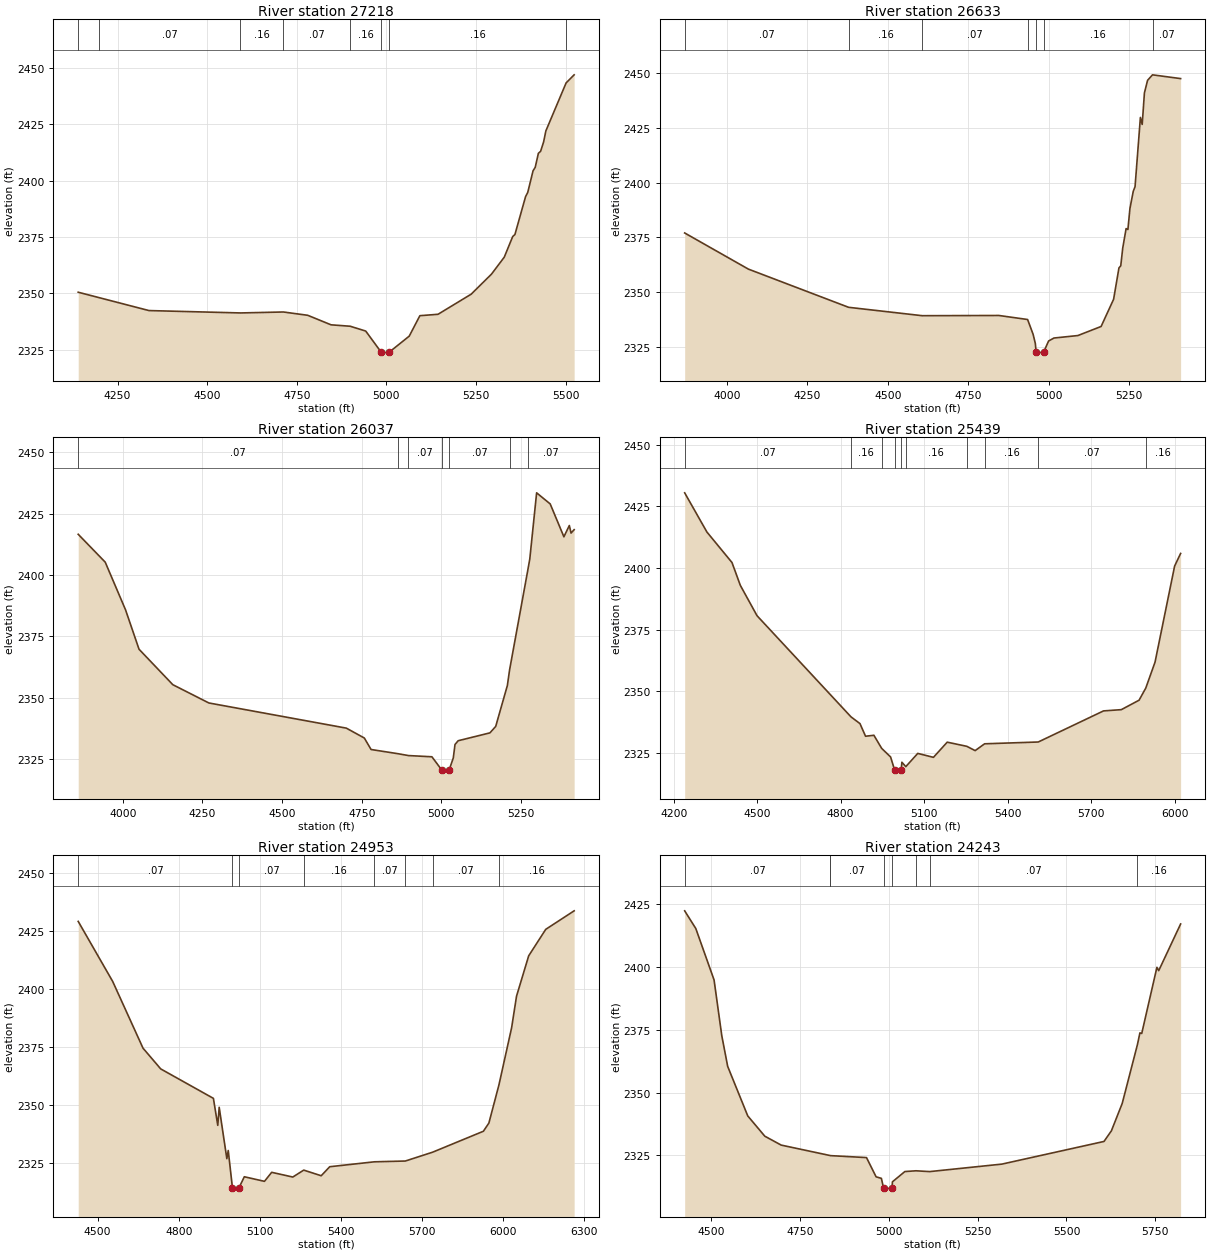
Type RM Length L Ch R = 1 ,27218   ,585,585,585
BEGIN DESCRIPTION:
Holder Creek 40.0
END DESCRIPTION:
XS GIS Cut Line= 3
        1411505.        6809138.      1411925.06       6808387.8
      1412354.96      6808088.03
#Sta/Elev= 30
  4140.2 2350.53  4199.2  2348.1  4337.7 2342.39    4593 2341.34  4712.7 2341.76
  4780.6  2340.3  4845.7 2336.07  4899.1 2335.44  4942.5  2333.3  4985.3 2324.01
  4985.8 2323.51  5008.7 2324.01  5063.9 2331.05  5093.6 2340.12  5144.2 2340.74
  5236.7 2349.66  5293.4 2358.55  5329.1 2366.09  5352.7 2375.26  5358.8 2376.12
  5388.5 2392.92  5394.6 2394.81  5409.4 2404.39  5415.5 2405.96  5424.3 2412.18
  5430.4 2413.02  5438.8 2417.16  5445.2 2422.12  5501.7 2443.41  5524.1 2446.99
#Mann= 8 ,-1 , 0
  4140.2     .16       0  4199.2     .07       0    4593     .16       0
  4712.7     .07       0  4899.1     .16       0  4985.3     .07       0
  5008.7     .16       0  5501.7     .07       0
Bank Sta=4985.3,5008.7
XS Rating Curve= 0 ,0
Exp/Cntr=0.3,0.1

Type RM Length L Ch R = 1 ,26633   ,596,596,596
BEGIN DESCRIPTION:
Holder Creek 39.0
END DESCRIPTION:
XS GIS Cut Line= 3
      1411355.02      6809537.98      1412140.52       6808724.8
      1412505.03      6808537.98
#Sta/Elev= 30
  3869.4 2376.98  4067.3 2360.46  4378.5 2343.01  4607.2 2339.18  4845.2 2339.28
  4934.4 2337.44  4951.5 2330.69  4958.4 2326.49  4960.9 2322.58  4961.4 2322.08
  4984.3 2322.58  4999.6 2327.62  5016.3 2328.98  5090.5 2330.11  5162.7 2334.26
  5201.5 2346.69  5218.1 2361.01  5223.7 2361.97  5229.8 2370.03  5240.3 2378.98
  5245.9 2378.57  5252.2 2388.16  5262.5 2396.01  5268.1 2398.12  5284.7 2429.76
  5290.3 2426.56  5297.2 2440.99  5306.9  2446.7  5322.3 2449.23  5409.6 2447.51
#Mann= 7 ,-1 , 0
  3869.4     .07       0  4378.5     .16       0  4607.2     .07       0
  4934.4     .16       0  4960.9     .07       0  4984.3     .16       0
  5322.3     .07       0
Bank Sta=4960.9,4984.3
XS Rating Curve= 0 ,0
Exp/Cntr=0.3,0.1

Type RM Length L Ch R = 1 ,26037   ,598,598,598
BEGIN DESCRIPTION:
Holder Creek 38.0
END DESCRIPTION:
XS GIS Cut Line= 3
        1411655.        6809988.      1412456.33      6809177.45
      1412605.01      6808787.96
#Sta/Elev= 30
  3860.2  2416.6    3945 2405.23  4008.7 2385.81  4051.1 2369.72  4157.2 2355.25
  4270.3  2347.8  4701.7 2337.54  4758.3  2333.5  4779.4 2328.82  4863.8 2327.11
  4896.6 2326.35  4970.4 2325.85  5001.1  2320.5  5001.6    2320  5024.6  2320.5
  5037.6 2325.41  5042.9 2330.86  5052.9  2332.4  5152.5  2335.6  5170.7 2338.24
  5207.3 2354.94  5214.3 2361.33  5270.8 2401.52  5277.7 2406.55  5299.1 2433.51
  5341.7 2428.99  5384.7 2415.58  5401.8 2420.18  5407.2 2417.09  5416.9 2418.48
#Mann= 7 ,-1 , 0
  3860.2     .07       0  4863.8     .16       0  4896.6     .07       0
  5001.1     .07       0  5024.6     .07       0  5214.3     .16       0
  5270.8     .07       0
Bank Sta=5001.1,5024.6
XS Rating Curve= 0 ,0
Exp/Cntr=0.3,0.1

Type RM Length L Ch R = 1 ,25439   ,486,486,486
BEGIN DESCRIPTION:
Holder Creek 37.0
END DESCRIPTION:
XS GIS Cut Line= 3
        1412505.      6810488.05      1412506.43      6809727.55
      1413155.01      6808937.98
#Sta/Elev= 30
  4239.5 2430.48  4319.5 2414.57  4409.5 2402.22  4439.5 2392.96  4499.5 2380.65
  4837.3 2339.62  4869.5 2336.89  4889.5 2331.77  4919.5 2332.16  4947.5 2326.84
  4979.5 2323.37  4993.9 2318.12  4994.4 2317.62  5017.7 2318.12  5020.1 2321.22
  5034.2 2319.44  5077.1 2324.81  5133.5 2323.21    5183 2329.36  5253.2 2327.69
  5283.4 2325.94  5317.4  2328.7  5510.1 2329.43  5744.8 2342.04  5808.7 2342.55
  5872.5 2346.38  5896.7 2351.33  5929.9 2361.83  6000.3 2400.79  6021.8  2405.9
#Mann= 10 ,-1 , 0
  4239.5     .07       0  4837.3     .16       0  4947.5     .07       0
  4993.9     .07       0  5017.7     .07       0  5034.2     .16       0
  5253.2     .07       0  5317.4     .16       0  5510.1     .07       0
  5896.7     .16       0
Bank Sta=4993.9,5017.7
XS Rating Curve= 0 ,0
Exp/Cntr=0.3,0.1

Type RM Length L Ch R = 1 ,24953   ,710,710,710
BEGIN DESCRIPTION:
Holder Creek 36.0
END DESCRIPTION:
XS GIS Cut Line= 3
      1412704.99      6810538.03      1412865.44        6809989.
        1413255.        6808788.
#Sta/Elev= 30
    4428 2429.06  4555.5 2403.24  4667.7 2374.53  4733.2  2365.6  4928.1 2352.93
  4944.3 2341.31  4949.5 2349.09  4977.8 2326.99    4983 2330.49  4998.6 2314.38
  4999.1 2313.88  5022.4 2314.38  5042.5  2319.2    5117 2317.23  5143.7 2321.11
  5221.8 2319.08  5262.3 2322.06  5326.9 2319.64  5358.5 2323.52  5523.5 2325.63
  5638.1 2325.97  5738.6 2329.75  5926.9 2338.78  5947.2 2342.31  5984.5 2358.78
  6031.3 2383.32  6049.5 2396.91  6094.4 2414.24  6157.5 2425.64  6262.6 2433.61
#Mann= 8 ,-1 , 0
    4428     .07       0  4998.6     .07       0  5022.4     .07       0
  5262.3     .16       0  5523.5     .07       0  5638.1     .16       0
  5738.6     .07       0  5984.5     .16       0
Bank Sta=4998.6,5022.4
XS Rating Curve= 0 ,0
Exp/Cntr=0.3,0.1

Type RM Length L Ch R = 1 ,24243   ,589,589,589
BEGIN DESCRIPTION:
Holder Creek 35.0
END DESCRIPTION:
XS GIS Cut Line= 3
      1413605.01      6810288.02      1413440.02      6809738.04
      1413254.99      6808937.96
#Sta/Elev= 30
  4425.8 2422.43  4457.1 2415.38  4508.5  2394.9  4530.2 2372.71  4546.8 2360.47
  4603.3 2340.74  4651.2 2332.67  4697.3 2329.12  4835.3 2324.95    4836 2324.92
  4937.4 2324.14  4964.4 2316.48  4979.2 2315.87  4985.4 2312.08  4985.9 2311.58
  5009.4 2312.08  5010.3 2314.48  5045.3 2318.58  5076.6 2318.88    5115 2318.56
  5318.2 2321.54  5605.6 2330.57  5626.4 2334.79  5656.9 2345.72  5699.7 2369.15
  5706.7 2373.82  5711.8 2373.58  5754.5 2399.92  5759.6  2398.6  5821.2 2417.19
#Mann= 8 ,-1 , 0
  4425.8     .07       0  4835.3     .16       0    4836     .07       0
  4985.4     .07       0  5009.4     .07       0  5076.6     .16       0
    5115     .07       0  5699.7     .16       0
Bank Sta=4985.4,5009.4
XS Rating Curve= 0 ,0
Exp/Cntr=0.3,0.1

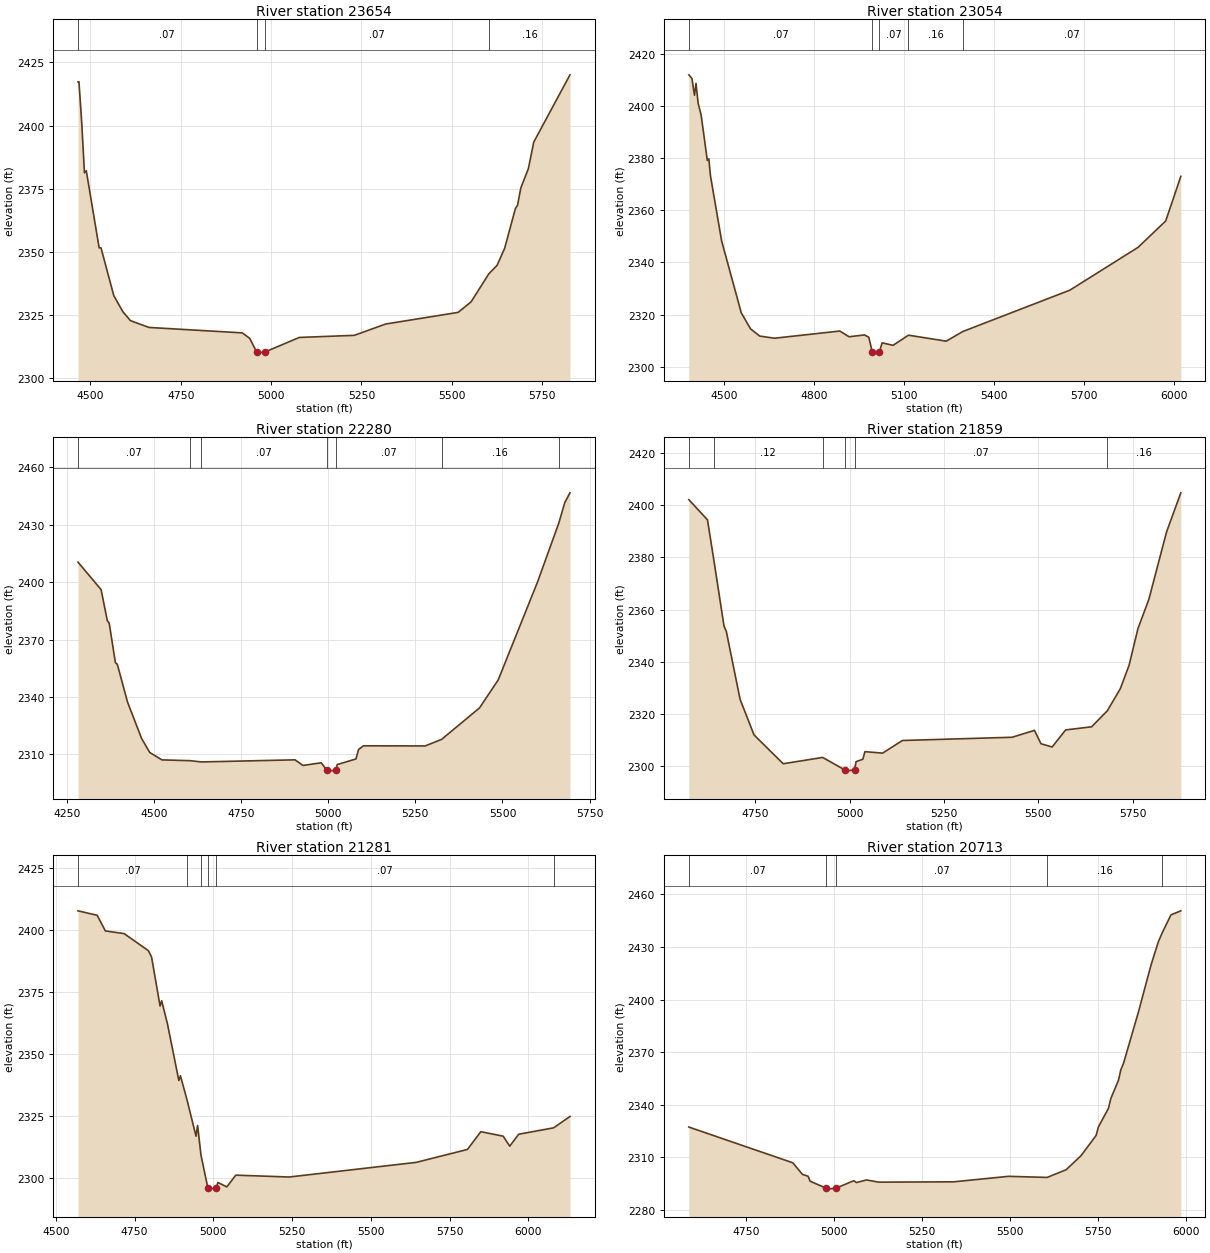
Type RM Length L Ch R = 1 ,23654   ,600,600,600
BEGIN DESCRIPTION:
Holder Creek 34.0
END DESCRIPTION:
XS GIS Cut Line= 3
      1414105.01      6810088.03      1413971.48      6809570.89
        1413505.        6808888.
#Sta/Elev= 30
  4465.9 2417.31  4468.5 2417.31  4476.3 2400.84  4483.7 2381.29  4488.8 2382.11
  4524.3 2351.68  4529.5 2351.62    4565 2332.69  4589.9  2326.4  4610.8 2322.86
  4662.2 2320.16  4920.4 2318.01    4941 2315.84    4960  2310.5  4960.5    2310
    4984  2310.5  5077.9  2316.2  5230.3 2317.03    5317 2321.51  5517.5 2326.11
  5553.4 2330.28  5602.7  2341.4  5625.2 2344.69  5646.1 2351.37    5676 2367.18
    5682 2368.49  5690.9 2375.27  5711.9 2382.97  5726.8 2393.47    5827 2420.06
#Mann= 4 ,-1 , 0
  4465.9     .07       0    4960     .07       0    4984     .07       0
  5602.7     .16       0
Bank Sta=4960,4984
XS Rating Curve= 0 ,0
Exp/Cntr=0.3,0.1

Type RM Length L Ch R = 1 ,23054   ,774,774,774
BEGIN DESCRIPTION:
Holder Creek 33.0
END DESCRIPTION:
XS GIS Cut Line= 3
      1414404.99      6810088.03      1414544.32      6809486.35
      1413754.97      6808837.97
#Sta/Elev= 30
  4382.4 2411.85  4392.7 2410.44  4401.2 2404.02  4406.3 2408.57  4413.2 2401.04
  4423.5 2396.33  4443.9 2379.06    4449 2379.67  4454.3 2373.27  4491.7 2348.19
  4556.9 2320.73  4587.7 2314.59  4618.5 2311.78  4667.6 2310.96  4885.4 2313.71
  4916.2 2311.52  4967.5 2312.22  4981.9 2311.33  4993.4 2305.75  4993.9 2305.25
  5017.4 2305.75  5026.3 2309.19  5062.8 2308.24    5114 2312.12  5240.1 2309.84
  5295.2 2313.53  5651.9 2329.37  5879.1 2345.77  5971.2 2355.88  6021.5 2372.96
#Mann= 5 ,-1 , 0
  4382.4     .07       0  4993.4     .07       0  5017.4     .07       0
    5114     .16       0  5295.2     .07       0
Bank Sta=4993.4,5017.4
XS Rating Curve= 0 ,0
Exp/Cntr=0.3,0.1

Type RM Length L Ch R = 1 ,22280   ,421,421,421
BEGIN DESCRIPTION:
Holder Creek 32.0
END DESCRIPTION:
XS GIS Cut Line= 3
      1414805.02      6810087.96      1415096.85      6809431.95
      1415355.01      6808787.96
#Sta/Elev= 30
    4282 2410.42  4348.3 2396.06  4366.1  2379.8  4371.5 2378.58  4389.3 2357.93
  4394.8 2357.06  4424.2 2337.28  4464.5 2318.32  4487.8 2311.02  4522.7 2307.13
  4603.5 2306.72  4636.3 2306.06  4904.8 2307.16  4927.7 2304.23    4980 2305.62
  4995.9 2301.76  4996.4 2301.26  5022.2 2301.76  5025.8 2304.68  5079.7 2307.62
  5087.1 2312.58  5101.2 2314.49  5278.1 2314.41  5325.5 2317.85  5434.1 2334.27
  5487.9 2348.92  5600.9 2400.15  5661.6 2430.77    5679 2441.58  5693.8 2446.64
#Mann= 7 ,-1 , 0
    4282     .07       0  4603.5     .12       0  4636.3     .07       0
  4995.9     .07       0  5022.2     .07       0  5325.5     .16       0
  5661.6     .07       0
Bank Sta=4995.9,5022.2
XS Rating Curve= 0 ,0
Exp/Cntr=0.3,0.1

Type RM Length L Ch R = 1 ,21859   ,578,578,578
BEGIN DESCRIPTION:
Holder Creek 31.0
END DESCRIPTION:
XS GIS Cut Line= 3
      1415005.01      6810137.99      1415255.06      6809792.97
      1415604.98      6808988.04
#Sta/Elev= 30
  4573.9 2402.09  4623.3 2394.37  4639.3 2379.75  4667.1 2353.68  4673.2 2351.65
  4709.7 2325.62  4746.7 2311.99    4824 2300.97  4928.6 2303.38  4986.8 2298.64
  4987.3 2298.14  5013.1 2298.64  5017.1 2301.77  5035.1 2302.69  5040.5  2305.6
  5087.4 2305.03  5139.8 2309.87  5430.7 2311.11  5489.8 2313.75    5507 2308.63
  5536.7 2307.38  5572.4 2313.91  5641.4 2315.12    5683 2321.27  5717.2 2329.65
  5740.6 2338.67  5764.1 2352.73    5793  2363.9  5839.9 2389.73  5877.7 2404.71
#Mann= 6 ,-1 , 0
  4573.9     .07       0  4639.3     .12       0  4928.6     .07       0
  4986.8     .07       0  5013.1     .07       0    5683     .16       0
Bank Sta=4986.8,5013.1
XS Rating Curve= 0 ,0
Exp/Cntr=0.3,0.1

Type RM Length L Ch R = 1 ,21281   ,568,568,568
BEGIN DESCRIPTION:
Holder Creek 30.0
END DESCRIPTION:
XS GIS Cut Line= 3
      1415004.99        6810238.      1415428.12      6810311.73
      1416205.01      6809487.99
#Sta/Elev= 30
  4570.5 2407.64  4631.4 2405.83  4657.3 2399.53  4716.9 2398.45  4793.8 2391.56
    4804    2389    4831  2369.2  4836.1 2371.33  4854.7 2361.86  4890.6 2339.13
  4895.7 2341.06  4915.9 2331.66  4945.1 2316.69  4950.2 2320.98  4960.9 2309.02
  4982.7 2295.81  4983.2 2295.31  5009.1 2295.81  5014.7 2297.99    5043 2296.22
  5071.3 2300.95  5240.8  2300.2  5644.2 2306.11  5806.8 2311.33  5849.3 2318.49
  5920.1 2316.69  5941.1 2312.66  5969.4 2317.46  6080.4 2320.05  6132.3 2324.64
#Mann= 6 ,-1 , 0
  4570.5     .07       0  4915.9     .12       0  4960.9     .07       0
  4982.7     .07       0  5009.1     .07       0  6080.4     .16       0
Bank Sta=4982.7,5009.1
XS Rating Curve= 0 ,0
Exp/Cntr=0.3,0.1

Type RM Length L Ch R = 1 ,20713   ,565,565,565
BEGIN DESCRIPTION:
Holder Creek 29.0
END DESCRIPTION:
XS GIS Cut Line= 3
      1415555.02      6810737.99      1415915.05      6810537.89
      1416654.98      6809888.02
#Sta/Elev= 30
  4588.1 2327.34  4883.2 2306.97  4910.6 2300.35  4926.7 2299.29  4932.4 2296.47
  4978.4 2292.45  4978.9 2291.95  5005.3 2292.45  5056.4 2296.76  5063.9  2295.7
  5092.4 2297.18  5127.5 2295.93  5340.1 2296.11  5495.7 2299.25  5605.3 2298.62
  5658.9 2302.97  5701.6 2311.03  5744.3 2322.56  5750.9 2327.45  5779.4 2338.04
    5786 2343.55  5807.9 2354.07  5814.5    2360  5822.1 2363.65  5864.8 2393.15
  5899.9  2419.5  5920.8 2432.86  5931.9 2438.08  5956.8 2448.33  5984.8 2450.63
#Mann= 5 ,-1 , 0
  4588.1     .07       0  4978.4     .07       0  5005.3     .07       0
  5605.3     .16       0  5931.9     .07       0
Bank Sta=4978.4,5005.3
XS Rating Curve= 0 ,0
Exp/Cntr=0.3,0.1