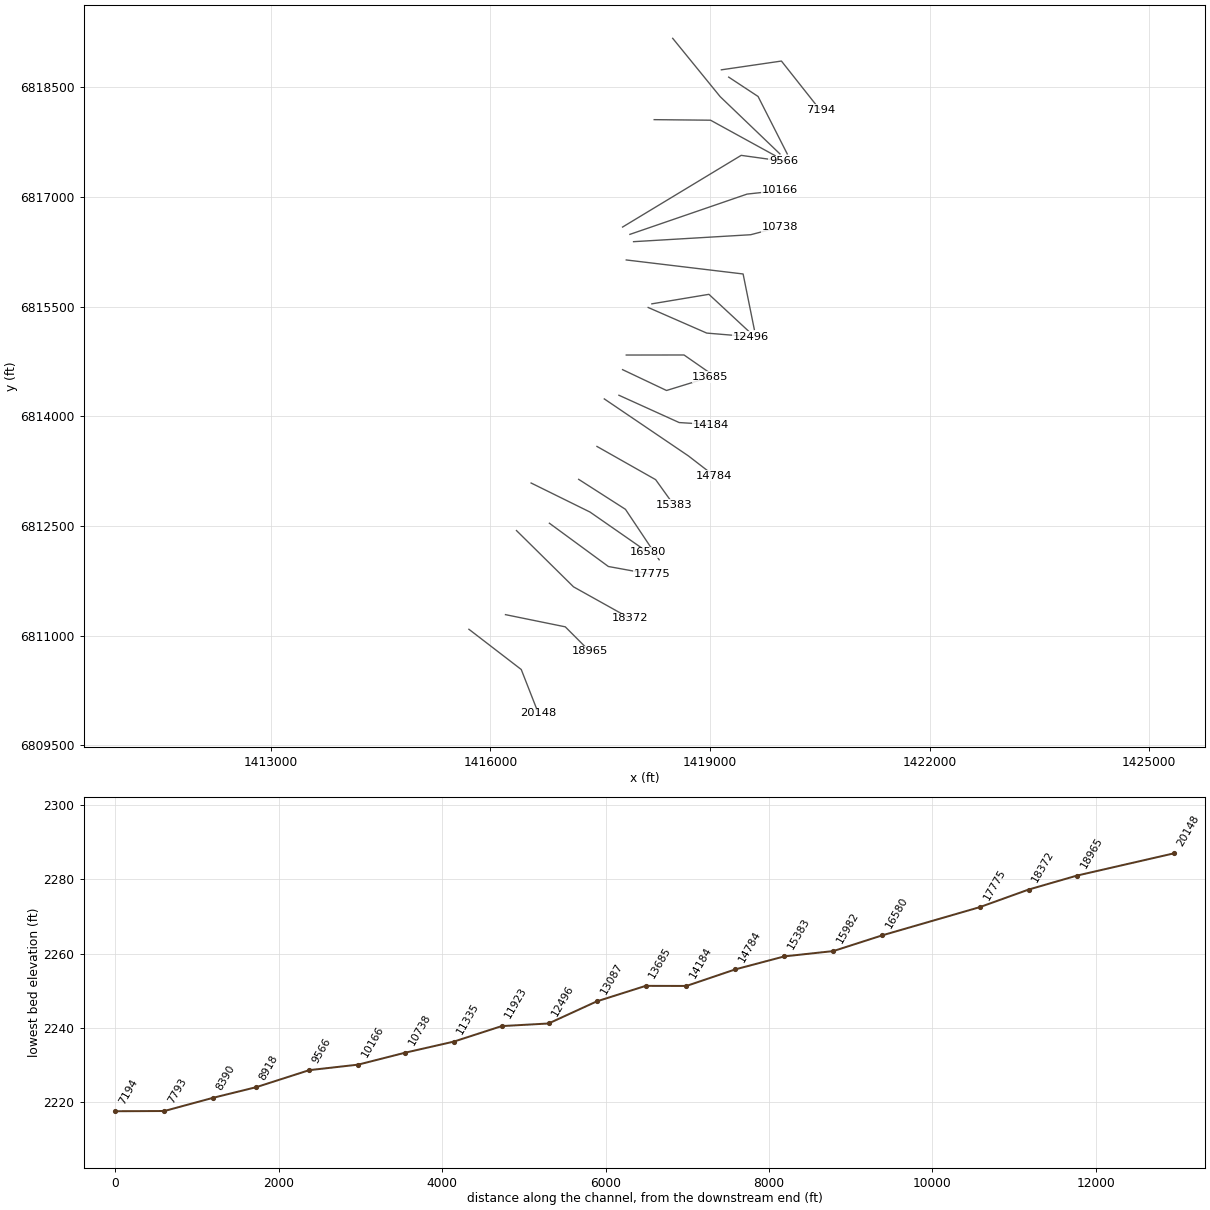
HEC-RAS study Holder Creek.prj: Holder Creek Base Level Engineering

--- Holder Creek.g01 (geometry) --- (continued)

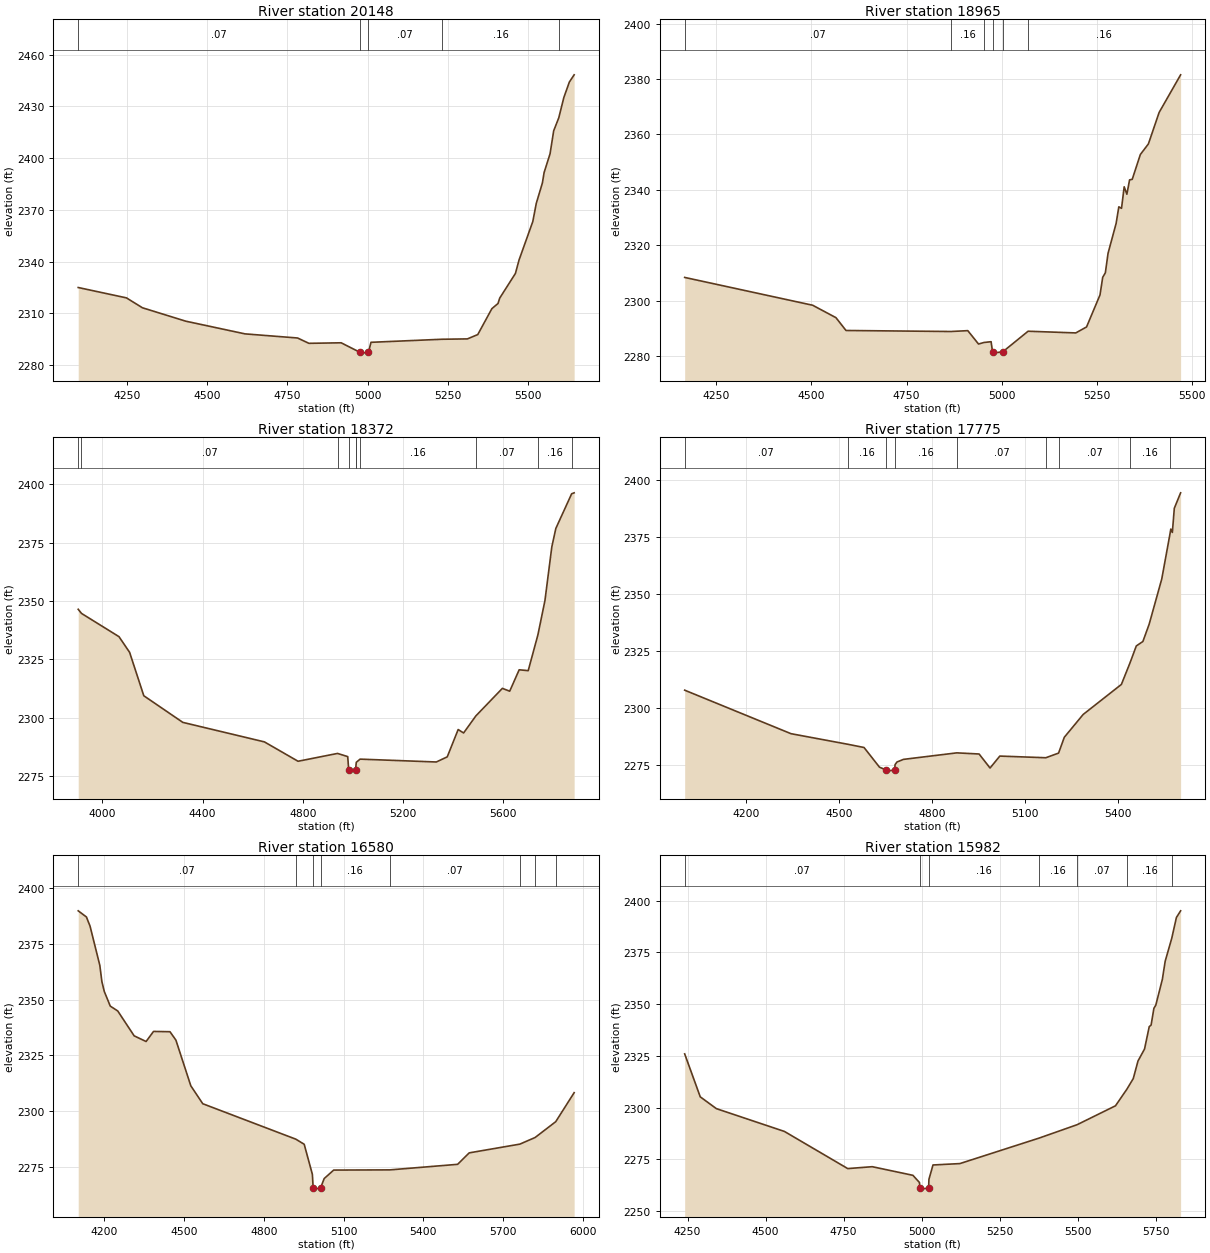
Type RM Length L Ch R = 1 ,20148   ,1183,1183,1183
BEGIN DESCRIPTION:
Holder Creek 28.0
END DESCRIPTION:
XS GIS Cut Line= 3
      1415705.01      6811087.99      1416420.37      6810537.76
      1416654.99      6809938.02
#Sta/Elev= 30
  4097.5 2325.01  4247.9    2319  4297.8 2313.26  4432.8 2305.49  4617.6 2298.13
  4781.6 2295.74  4816.9 2292.65  4917.5 2292.96  4975.7 2287.47  4976.2 2286.97
  5002.7 2287.47  5010.5 2293.24  5231.9 2295.01  5311.1 2295.22  5343.4 2297.72
  5387.5 2312.76  5406.6 2315.76  5411.9 2318.87  5460.9 2333.17  5472.2 2340.98
  5515.1 2363.28  5525.9  2373.8    5545 2385.64  5550.3 2391.66  5568.9 2402.56
  5580.2 2415.87  5596.1 2423.42  5611.8 2435.12  5629.1 2444.15    5644 2448.31
#Mann= 5 ,-1 , 0
  4097.5     .07       0  4975.7     .07       0  5002.7     .07       0
  5231.9     .16       0  5596.1     .07       0
Bank Sta=4975.7,5002.7
XS Rating Curve= 0 ,0
Exp/Cntr=0.3,0.1

Type RM Length L Ch R = 1 ,18965   ,593,593,593
BEGIN DESCRIPTION:
Holder Creek 27.0
END DESCRIPTION:
XS GIS Cut Line= 3
      1416204.99        6811288.      1417021.88      6811121.42
      1417354.99      6810788.01
#Sta/Elev= 30
  4166.3 2308.35  4503.1  2298.3  4564.3 2293.82  4590.8 2289.18    4867 2288.81
  4911.3 2289.12  4939.5 2284.29  4953.8 2284.84  4972.6 2285.13  4976.4  2281.5
  4976.9    2281  5003.5  2281.5    5070 2288.91  5195.5  2288.3  5223.8 2290.46
  5259.2 2302.04  5266.3 2308.39  5273.3 2310.05  5280.4  2317.1  5301.6 2327.87
  5308.7 2333.86  5315.8 2333.31  5322.8  2341.1  5329.9 2338.41    5337 2343.59
    5344  2343.8  5365.3 2352.75  5386.5 2356.58  5414.8 2367.97  5471.3 2381.55
#Mann= 6 ,-1 , 0
  4166.3     .07       0    4867     .16       0  4953.8     .12       0
  4976.4     .07       0  5003.5     .12       0    5070     .16       0
Bank Sta=4976.4,5003.5
XS Rating Curve= 0 ,0
Exp/Cntr=0.3,0.1

Type RM Length L Ch R = 1 ,18372   ,597,597,597
BEGIN DESCRIPTION:
Holder Creek 26.0
END DESCRIPTION:
XS GIS Cut Line= 3
      1416355.04      6812437.97      1417134.82      6811668.08
      1417904.97      6811238.01
#Sta/Elev= 30
  3904.2 2346.46  3917.3 2344.69  4066.8 2334.75  4109.2 2328.04  4165.8 2309.47
  4321.4 2298.08  4646.7 2289.74    4781 2281.45  4938.4  2284.8    4979 2283.45
  4983.1 2277.73  4983.6 2277.23  5010.2 2277.73  5013.2    2281  5028.4 2282.36
  5332.4 2281.14    5376 2283.33  5419.5 2295.02  5441.2 2293.55    5490 2300.83
  5595.8 2312.63  5625.1 2311.42  5662.8 2320.57  5698.9 2320.21  5737.5  2335.5
  5765.6 2350.18    5793 2373.13    5809 2381.02  5872.1 2395.86  5882.1 2396.27
#Mann= 10 ,-1 , 0
  3904.2    .035       0  3917.3     .07       0  4938.4     .16       0
  4983.1     .07       0  5010.2     .16       0  5013.2     .07       0
  5028.4     .16       0    5490     .07       0  5737.5     .16       0
  5872.1     .07       0
Bank Sta=4983.1,5010.2
XS Rating Curve= 0 ,0
Exp/Cntr=0.3,0.1

Type RM Length L Ch R = 1 ,17775   ,1195,1195,1195
BEGIN DESCRIPTION:
Holder Creek 25.0
END DESCRIPTION:
XS GIS Cut Line= 3
      1416804.96      6812538.03      1417610.94      6811946.42
      1418205.03        6811838.
#Sta/Elev= 30
  4000.2    2308    4344 2288.92  4526.8  2284.3  4580.2 2282.86  4630.3 2274.21
  4652.1    2273  4652.6  2272.5  4679.5    2273  4680.5 2275.33  4686.7  2276.5
  4707.6 2277.65  4880.2 2280.51  4952.2 2280.01  4987.7 2273.86  5019.2  2279.1
  5168.1 2278.37  5209.3 2280.41  5227.8 2287.35  5288.8 2297.35  5412.4 2310.53
  5440.6 2320.09  5460.6  2327.4  5481.9 2329.34  5502.2 2336.93  5542.9 2356.75
  5569.9  2376.8  5572.2 2378.65  5577.2 2377.18  5583.5 2387.75  5603.9 2394.54
#Mann= 9 ,-1 , 0
  4000.2     .07       0  4526.8     .16       0  4652.1     .07       0
  4679.5     .16       0  4880.2     .07       0  5168.1     .16       0
  5209.3     .07       0  5440.6     .16       0  5569.9     .07       0
Bank Sta=4652.1,4679.5
XS Rating Curve= 0 ,0
Exp/Cntr=0.3,0.1

Type RM Length L Ch R = 1 ,16580   ,598,598,598
BEGIN DESCRIPTION:
Holder Creek 24.0
END DESCRIPTION:
XS GIS Cut Line= 3
      1416555.01      6813087.99      1417360.46      6812690.48
      1418154.96      6812138.03
#Sta/Elev= 30
  4101.8 2389.81  4132.7 2387.05  4146.4 2382.92  4183.1 2365.33    4191 2357.96
    4200 2353.58  4222.5 2347.03  4250.5 2344.87  4312.3  2333.7  4357.2 2331.16
  4385.2 2335.68    4447 2335.55  4469.4 2331.77  4525.5 2311.26  4570.4 2303.23
  4920.4 2287.33    4952 2285.04  4982.8 2271.55  4985.8  2265.4  4986.3  2264.9
  5013.6  2265.4  5027.2 2269.64    5063 2273.45  5274.9 2273.54  5529.3 2276.03
  5572.8 2281.17  5763.4  2285.1  5820.7 2288.06  5898.4 2295.17  5967.7 2308.19
#Mann= 8 ,-1 , 0
  4101.8     .07       0  4920.4     .16       0  4985.8     .07       0
  5013.6     .16       0  5274.9     .07       0  5763.4     .16       0
  5820.7     .07       0  5898.4     .16       0
Bank Sta=4985.8,5013.6
XS Rating Curve= 0 ,0
Exp/Cntr=0.3,0.1

Type RM Length L Ch R = 1 ,15982   ,599,599,599
BEGIN DESCRIPTION:
Holder Creek 23.0
END DESCRIPTION:
XS GIS Cut Line= 3
      1417204.97      6813138.02      1417844.22      6812728.28
      1418304.98      6812038.03
#Sta/Elev= 30
  4240.7 2325.98  4290.6 2305.24  4342.2 2299.54  4560.3 2288.53  4763.2 2270.59
  4841.8  2271.5    4972 2267.34  4993.1 2263.86  4994.4 2261.17  4994.9 2260.67
  5022.3 2261.17  5023.4  2265.4  5036.4 2272.33  5122.5    2273  5377.3 2285.36
  5498.2 2291.78  5621.2 2300.91  5658.4 2309.08  5678.2 2314.06  5693.3 2322.54
  5714.3 2328.34  5729.3 2339.11  5735.3 2339.88  5744.3    2348  5750.3 2349.47
  5771.4 2361.97  5780.4  2370.7  5801.5  2381.8  5816.4 2391.83  5829.9 2395.06
#Mann= 7 ,-1 , 0
  4240.7     .07       0  4994.4     .07       0  5022.3     .16       0
  5377.3     .16       0  5498.2     .07       0  5658.4     .16       0
  5801.5     .07       0
Bank Sta=4994.4,5022.3
XS Rating Curve= 0 ,0
Exp/Cntr=0.3,0.1

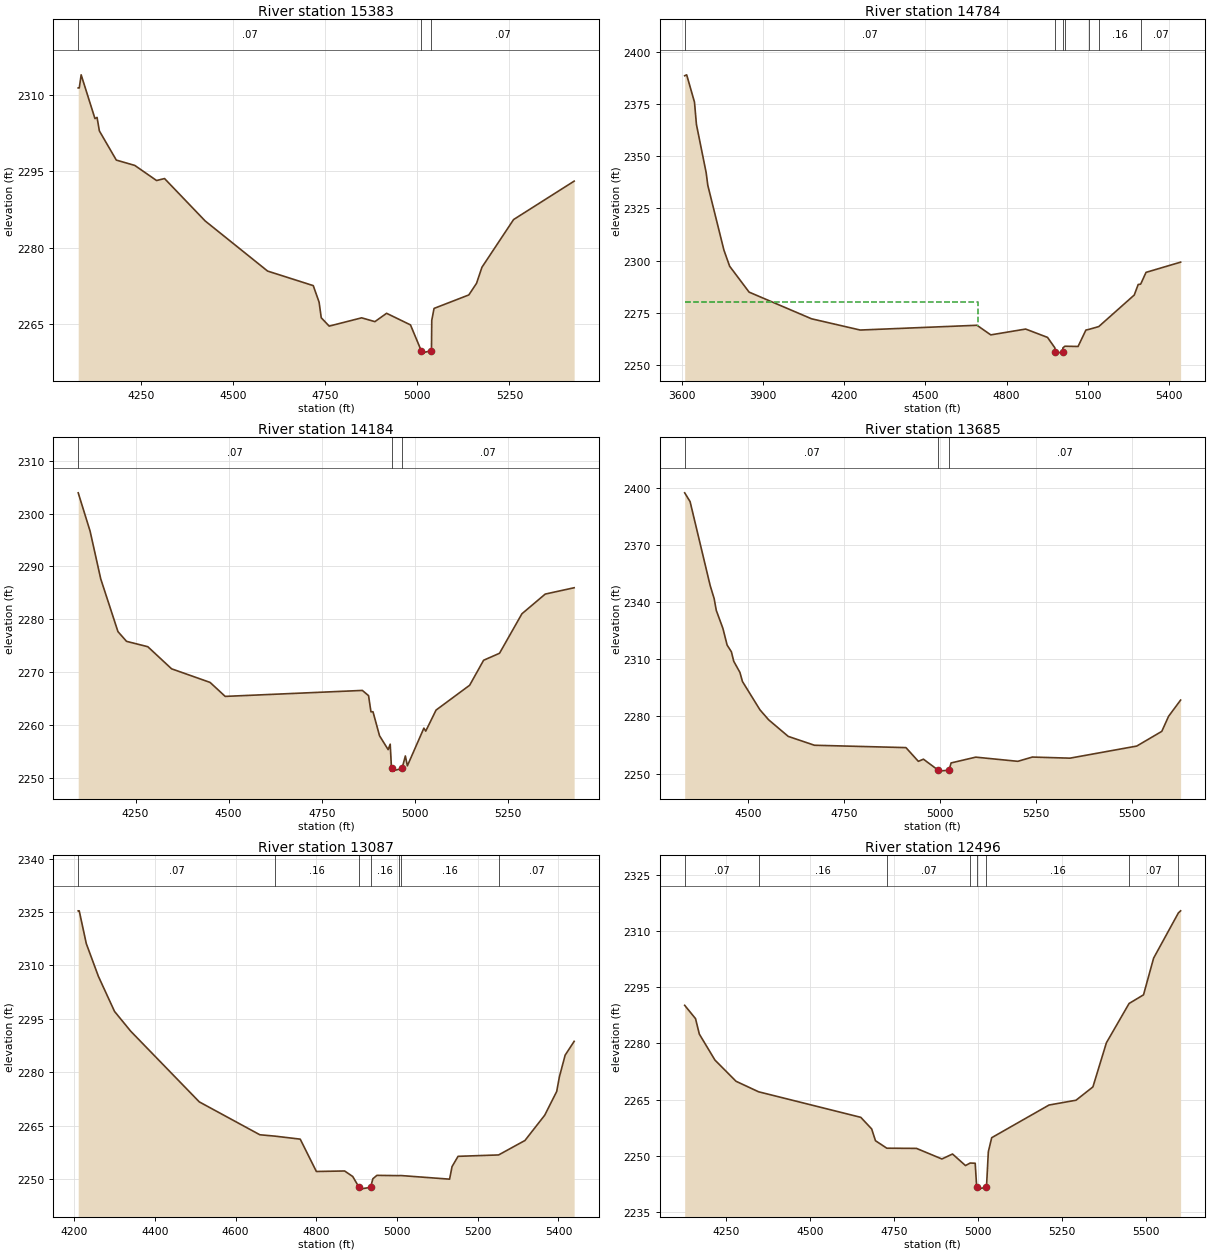
Type RM Length L Ch R = 1 ,15383   ,599,599,599
BEGIN DESCRIPTION:
Holder Creek 22.0
END DESCRIPTION:
XS GIS Cut Line= 3
      1417454.98      6813588.01      1418256.65      6813134.01
      1418504.99      6812788.01
#Sta/Elev= 30
  4078.7 2311.37  4081.6 2311.37  4086.7 2313.95  4124.2 2305.35  4129.9 2305.58
  4136.2 2302.92  4182.2 2297.19  4232.4 2296.14  4291.6 2293.17  4313.2 2293.56
  4423.5 2285.23  4593.2 2275.37  4717.2 2272.51  4733.1 2269.25  4738.9 2266.19
  4760.5 2264.55  4848.7 2266.18  4884.6 2265.43  4916.4 2267.07  4981.3 2264.79
  5010.4 2259.74  5010.9 2259.24  5038.3 2259.74  5039.1 2265.68  5045.3 2268.03
  5139.8 2270.68  5160.7 2272.96  5175.4 2276.12  5261.4  2285.5  5425.9 2293.05
#Mann= 3 ,-1 , 0
  4078.7     .07       0  5010.4     .07       0  5038.3     .07       0
Bank Sta=5010.4,5038.3
XS Rating Curve= 0 ,0
Exp/Cntr=0.3,0.1

Type RM Length L Ch R = 1 ,14784   ,600,600,600
BEGIN DESCRIPTION:
Holder Creek 21.0
END DESCRIPTION:
XS GIS Cut Line= 3
      1417555.03      6814237.98      1418704.52       6813458.4
      1419055.02      6813187.98
#Sta/Elev= 30
  3611.1  2388.5  3618.5 2388.94  3647.3 2375.89  3654.5 2365.19  3690.4 2342.14
  3696.5 2336.07  3756.1 2305.02  3777.2 2297.34  3849.1 2284.94  4079.7 2272.18
  4259.4  2266.8  4690.7 2269.08  4741.6 2264.48  4870.4 2267.27  4951.2 2263.28
  4978.2 2258.31  4979.2 2256.25  4979.7 2255.75  5007.2 2256.25  5007.9 2258.25
  5015.2 2259.05    5064 2258.94    5093 2266.81  5102.7 2267.06  5140.3 2268.45
  5271.5 2283.56    5286  2288.6  5295.1 2288.76    5315  2294.4  5442.7 2299.29
#Mann= 7 ,-1 , 0
  3611.1     .07       0  4979.2     .07       0  5007.2     .07       0
  5015.2     .16       0  5102.7     .07       0  5140.3     .16       0
  5295.1     .07       0
#XS Ineff= 2 , 0
         4695.01 2280.08
Permanent Ineff=
       F       F
Bank Sta=4979.2,5007.2
XS Rating Curve= 0 ,0
Exp/Cntr=0.3,0.1

Type RM Length L Ch R = 1 ,14184   ,499,499,499
BEGIN DESCRIPTION:
Holder Creek 20.0
END DESCRIPTION:
XS GIS Cut Line= 3
      1417754.98      6814288.01      1418578.27      6813914.64
      1419005.04        6813888.
#Sta/Elev= 30
    4096 2303.94  4127.9 2296.69  4156.5 2287.65  4202.7 2277.68  4225.7 2275.84
  4282.9 2274.82  4346.7 2270.64    4450 2268.07  4490.7 2265.42  4858.9 2266.55
  4875.6 2265.56    4882 2262.51  4887.5 2262.51  4905.1 2257.97  4928.2 2255.35
  4933.7 2256.38  4937.2 2251.78  4937.7 2251.28  4965.4 2251.78  4974.4 2254.15
  4979.8 2252.28  5024.1 2259.41  5029.1 2258.85  5056.8 2262.83    5147 2267.53
  5184.5 2272.26  5227.2 2273.58  5287.3 2281.05  5349.9 2284.78  5427.6 2285.98
#Mann= 3 ,-1 , 0
    4096     .07       0  4937.2     .07       0  4965.4     .07       0
Bank Sta=4937.2,4965.4
XS Rating Curve= 0 ,0
Exp/Cntr=0.3,0.1

Type RM Length L Ch R = 1 ,13685   ,598,598,598
BEGIN DESCRIPTION:
Holder Creek 19.0
END DESCRIPTION:
XS GIS Cut Line= 3
      1417805.02      6814637.99      1418405.52      6814353.22
      1419004.99        6814538.
#Sta/Elev= 30
  4335.4 2397.46  4349.5 2392.84  4401.8 2348.77  4412.2 2341.91  4417.7 2335.73
  4434.9 2326.32    4446 2317.49  4457.1 2313.97  4463.2 2309.01  4479.3 2303.15
  4485.9 2298.38  4531.4 2283.52  4554.1 2278.26  4605.1 2269.55  4673.4 2264.89
  4911.8 2263.65  4944.1 2256.44  4957.3 2257.58  4995.8  2251.8  4996.3  2251.3
    5024  2251.8  5029.4  2255.6  5093.6 2258.64  5203.2 2256.45  5241.1 2258.69
  5339.1 2258.11    5513 2264.46  5578.3 2272.19  5595.9 2280.08  5627.3 2288.61
#Mann= 3 ,-1 , 0
  4335.4     .07       0  4995.8     .07       0    5024     .07       0
Bank Sta=4995.8,5024
XS Rating Curve= 0 ,0
Exp/Cntr=0.3,0.1

Type RM Length L Ch R = 1 ,13087   ,591,591,591
BEGIN DESCRIPTION:
Holder Creek 18.0
END DESCRIPTION:
XS GIS Cut Line= 3
      1417855.01        6814838.      1418644.81      6814838.55
      1419005.03      6814587.98
#Sta/Elev= 30
  4210.2 2325.36  4212.7 2325.36  4230.2 2316.16  4260.2 2306.94  4300.2 2297.08
  4340.2 2291.53  4510.2 2271.65  4660.2 2262.41  4698.1 2262.02  4760.2 2261.18
  4800.2 2252.09  4870.2 2252.23  4890.2 2250.69    4906 2247.63  4906.5 2247.13
  4934.4 2247.63  4940.2 2250.05  4950.2    2251  5004.3 2250.92  5009.4 2250.95
  5130.2 2249.93  5136.3 2253.46  5151.2 2256.35  5251.6 2256.74  5316.9  2260.8
  5365.9 2267.91  5395.6 2274.59  5402.2 2278.69  5416.5 2284.79  5438.8 2288.67
#Mann= 7 ,-1 , 0
  4210.2     .07       0  4698.1     .16       0    4906     .07       0
  4934.4     .16       0  5004.3     .07       0  5009.4     .16       0
  5251.6     .07       0
Bank Sta=4906,4934.4
XS Rating Curve= 0 ,0
Exp/Cntr=0.3,0.1

Type RM Length L Ch R = 1 ,12496   ,573,573,573
BEGIN DESCRIPTION:
Holder Creek 17.0
END DESCRIPTION:
XS GIS Cut Line= 3
      1418155.03      6815487.99      1418954.92      6815138.03
      1419555.04        6815088.
#Sta/Elev= 30
  4126.9 2290.17  4159.2 2286.62  4170.5  2282.5  4216.9 2275.58  4279.7 2269.92
  4346.7 2267.12  4650.8 2260.31  4683.2 2257.21  4694.5 2254.07  4728.2 2252.08
  4816.5 2252.03  4892.1 2249.21  4923.7 2250.53  4962.3 2247.45  4976.2 2248.13
  4991.1 2248.07  4995.6 2241.67  4996.1 2241.17  5024.7 2241.67  5030.2 2251.14
  5040.2 2254.88  5210.8 2263.59  5291.1 2264.87  5341.3 2268.42  5381.4 2280.18
  5448.9 2290.66  5491.8 2292.96  5521.9 2302.76  5595.6 2314.81  5602.2 2315.36
#Mann= 8 ,-1 , 0
  4126.9     .07       0  4346.7     .16       0  4728.2     .07       0
  4976.2     .16       0  4995.6     .07       0  5024.7     .16       0
  5448.9     .07       0  5595.6     .16       0
Bank Sta=4995.6,5024.7
XS Rating Curve= 0 ,0
Exp/Cntr=0.3,0.1

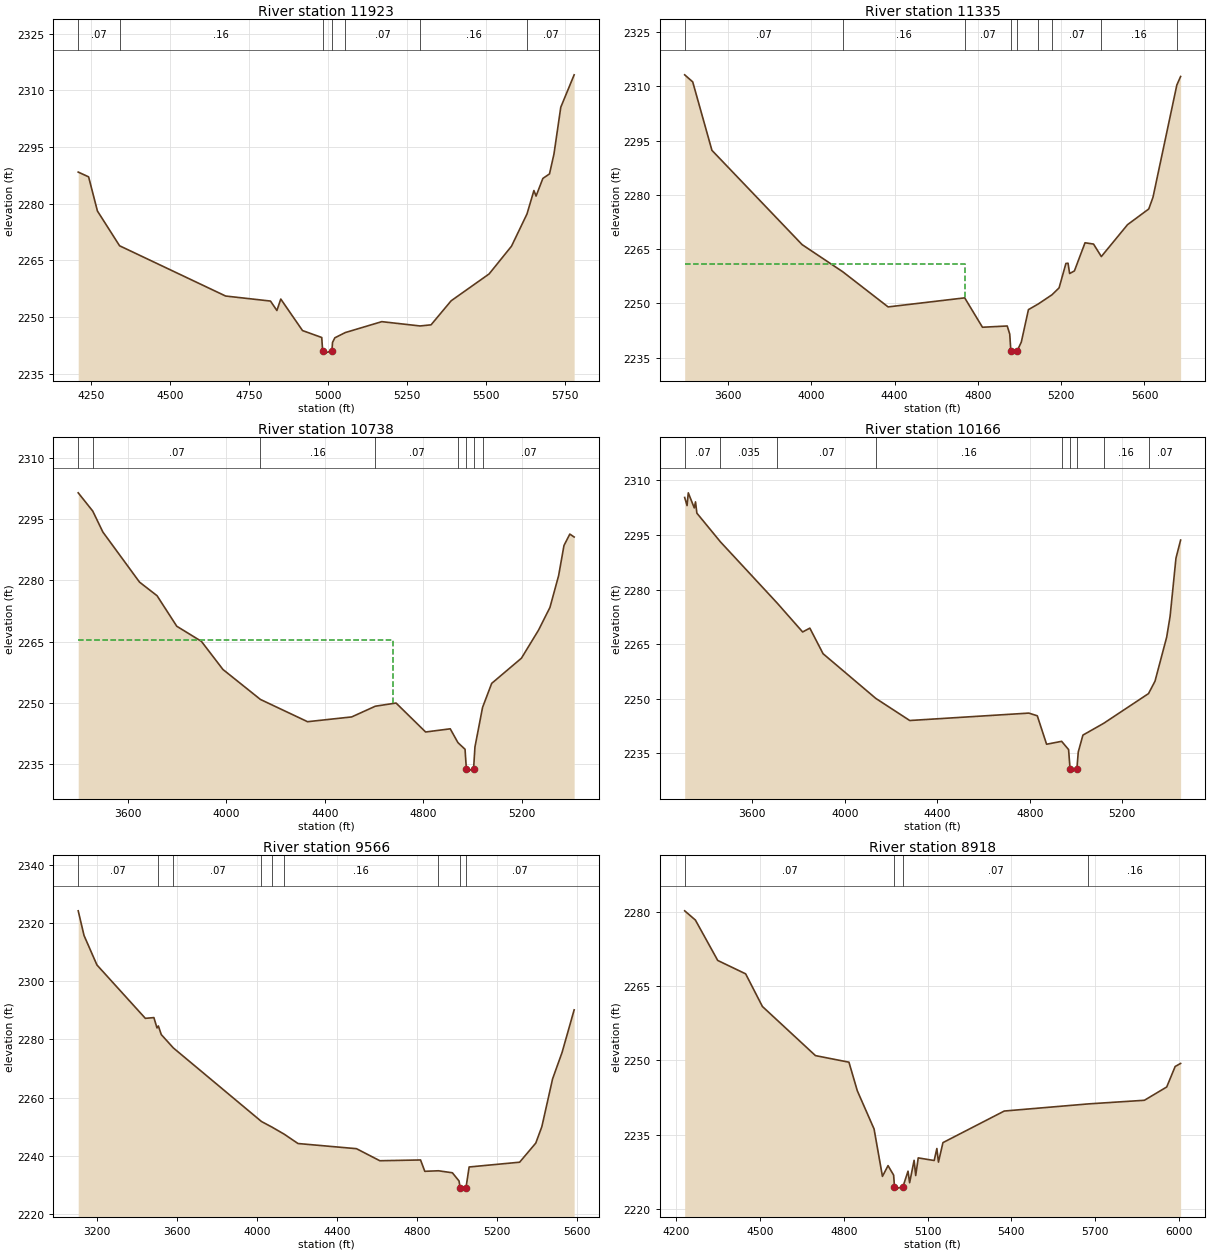
Type RM Length L Ch R = 1 ,11923   ,588,588,588
BEGIN DESCRIPTION:
Holder Creek 16.0
END DESCRIPTION:
XS GIS Cut Line= 3
      1418204.99        6815538.      1418984.61      6815668.08
      1419555.02      6815137.98
#Sta/Elev= 30
  4209.6 2288.38  4242.5 2287.12  4270.4 2278.08  4340.5 2268.88    4676 2255.58
  4817.9 2254.25  4838.2 2251.75  4850.5 2254.78  4919.3 2246.44  4980.1 2244.61
  4983.1 2240.97  4983.6 2240.47  5012.2 2240.97  5014.2  2243.3  5021.6 2244.53
  5054.5 2245.91  5170.1  2248.8  5291.2 2247.66    5326 2247.96  5389.5 2254.32
  5509.7 2261.43  5580.5 2268.77  5629.5  2277.3  5651.4  2283.5  5658.2 2282.03
  5679.7  2286.7  5700.7  2287.9  5714.9 2293.19  5736.4 2305.55  5778.7 2314.12
#Mann= 7 ,-1 , 0
  4209.6     .07       0  4340.5     .16       0  4983.1     .07       0
  5012.2     .16       0  5054.5     .07       0  5291.2     .16       0
  5629.5     .07       0
Bank Sta=4983.1,5012.2
XS Rating Curve= 0 ,0
Exp/Cntr=0.3,0.1

Type RM Length L Ch R = 1 ,11335   ,597,597,597
BEGIN DESCRIPTION:
Holder Creek 15.0
END DESCRIPTION:
XS GIS Cut Line= 3
      1417855.01        6816138.      1419451.85      6815946.32
      1419604.99      6815188.03
#Sta/Elev= 30
  3391.7 2313.17  3430.3 2311.22  3522.6 2292.31  3955.7 2266.26  4150.9 2258.76
  4368.7 2249.05  4736.6 2251.55  4821.9 2243.43  4940.8 2243.78  4952.8 2241.57
  4958.4 2236.78  4958.9 2236.28  4987.5 2236.78  5008.5 2239.33  5042.7  2248.3
  5089.9 2249.86    5156 2252.41  5189.9 2254.31  5222.7 2261.05  5232.9 2261.13
  5240.6 2258.27  5263.5 2258.99  5314.5 2266.77  5355.4 2266.41  5392.8 2262.96
  5518.6 2271.77  5620.6 2276.11    5641 2279.36  5755.4 2310.35  5773.6 2312.71
#Mann= 9 ,-1 , 0
  3391.7     .07       0  4150.9     .16       0  4736.6     .07       0
  4958.4     .07       0  4987.5     .07       0  5089.9     .16       0
    5156     .07       0  5392.8     .16       0  5755.4     .07       0
#XS Ineff= 2 , 0
         4738.69 2260.95
Permanent Ineff=
       F       F
Bank Sta=4958.4,4987.5
XS Rating Curve= 0 ,0
Exp/Cntr=0.3,0.1

Type RM Length L Ch R = 1 ,10738   ,572,572,572
BEGIN DESCRIPTION:
Holder Creek 14.0
END DESCRIPTION:
XS GIS Cut Line= 3
      1417955.01        6816388.      1419555.09      6816482.96
      1419955.03      6816588.01
#Sta/Elev= 30
  3397.1 2301.42  3456.2 2296.95  3497.3 2291.83  3646.4 2279.56  3717.7 2276.23
  3797.8 2268.76    3898 2265.06  3985.5 2258.18  4137.9 2250.84  4329.6 2245.39
    4509 2246.56  4605.1 2249.18  4689.4 2249.96  4809.6 2242.87  4909.7 2243.65
  4941.1 2240.26  4969.9 2238.64  4975.3 2233.79  4975.8 2233.29  5004.5 2233.79
  5010.2 2239.21  5041.1 2248.88  5078.2 2254.77  5199.2 2260.94  5268.7 2267.81
  5315.2 2273.38  5350.3 2281.13  5372.1 2288.52  5395.9 2291.32  5413.5  2290.6
#Mann= 8 ,-1 , 0
  3397.1    .035       0  3456.2     .07       0  4137.9     .16       0
  4605.1     .07       0  4941.1     .16       0  4975.3     .07       0
  5004.5     .16       0  5041.1     .07       0
#XS Ineff= 2 , 0
         4677.07 2265.31
Permanent Ineff=
       F       F
Bank Sta=4975.3,5004.5
XS Rating Curve= 0 ,0
Exp/Cntr=0.3,0.1

Type RM Length L Ch R = 1 ,10166   ,600,600,600
BEGIN DESCRIPTION:
Holder Creek 13.0
END DESCRIPTION:
XS GIS Cut Line= 3
      1417905.03      6816488.01       1419505.5      6817038.51
      1419954.99        6817088.
#Sta/Elev= 30
  3307.5 2305.31  3317.8 2303.08  3323.1 2306.58    3349 2302.43  3354.3  2304.1
  3360.3 2300.99  3461.8 2293.13  3707.1 2276.31  3817.6 2268.34  3848.8 2269.39
    3906 2262.36    4134 2250.08  4280.8    2244  4795.9 2246.04  4832.4  2245.3
  4872.6 2237.48  4937.6 2238.28  4967.7 2236.02  4974.2 2230.59  4974.7 2230.09
  5003.5 2230.59  5009.6 2235.36  5029.7 2239.99  5119.5 2243.23  5313.4  2251.4
  5341.5 2254.82  5391.9 2266.91  5406.7 2272.63  5432.1 2288.63  5452.2 2293.59
#Mann= 9 ,-1 , 0
  3307.5     .07       0  3461.8    .035       0  3707.1     .07       0
    4134     .16       0  4937.6     .07       0  4974.2     .07       0
  5003.5     .07       0  5119.5     .16       0  5313.4     .07       0
Bank Sta=4974.2,5003.5
XS Rating Curve= 0 ,0
Exp/Cntr=0.3,0.1

Type RM Length L Ch R = 1 ,9566    ,648,648,648
BEGIN DESCRIPTION:
Holder Creek 12.0
END DESCRIPTION:
XS GIS Cut Line= 3
      1417804.98      6816587.99      1419425.49       6817568.2
      1420004.97        6817488.
#Sta/Elev= 30
  3106.1 2324.11  3135.2 2315.65  3199.6 2305.54  3441.7 2287.21  3484.4 2287.47
  3499.9 2283.92  3506.8 2284.59  3521.3 2281.64  3581.6 2277.06  4022.1 2251.81
  4074.5 2249.89  4135.9 2247.45  4204.7 2244.25  4496.9 2242.48  4613.8 2238.34
  4817.2 2238.61  4838.5 2234.71  4906.6  2234.9  4976.3 2234.21  5009.6 2231.39
  5015.1  2229.1  5015.6  2228.6  5044.4  2229.1  5060.1  2236.2  5312.5 2237.84
  5393.2  2244.4  5423.5 2250.03  5477.3 2266.46  5524.5 2275.48    5585 2290.12
#Mann= 9 ,-1 , 0
  3106.1     .07       0  3506.8    .035       0  3581.6     .07       0
  4022.1     .16       0  4074.5     .07       0  4135.9     .16       0
  4906.6     .07       0  5015.1     .07       0  5044.4     .07       0
Bank Sta=5015.1,5044.4
XS Rating Curve= 0 ,0
Exp/Cntr=0.3,0.1

Type RM Length L Ch R = 1 ,8918    ,528,528,528
BEGIN DESCRIPTION:
Holder Creek 11.1
END DESCRIPTION:
XS GIS Cut Line= 3
      1418236.64      6818056.54       1419006.7      6818049.02
      1419888.67      6817564.48
#Sta/Elev= 30
  4229.9 2280.15  4268.3 2278.29  4348.3 2270.14  4448.3 2267.44  4508.3 2260.86
  4698.3 2250.95  4818.3 2249.62  4848.3 2243.85  4908.3 2236.15  4938.3 2226.59
  4958.3 2228.76  4978.3 2226.85  4981.4 2224.52  4981.9 2224.02  5011.8 2224.52
  5029.9 2227.64  5035.6 2225.31  5051.7 2229.83  5057.4 2226.76  5066.5 2230.32
  5123.6 2229.79  5133.2 2232.21  5138.9 2229.47    5155  2233.4  5374.6 2239.77
  5676.3 2241.21  5876.6 2241.94  5956.5 2244.62  5986.8 2248.76  6006.3 2249.37
#Mann= 4 ,-1 , 0
  4229.9     .07       0  4981.4     .07       0  5011.8     .07       0
  5676.3     .16       0
Bank Sta=4981.4,5011.8
XS Rating Curve= 0 ,0
Exp/Cntr=0.3,0.1

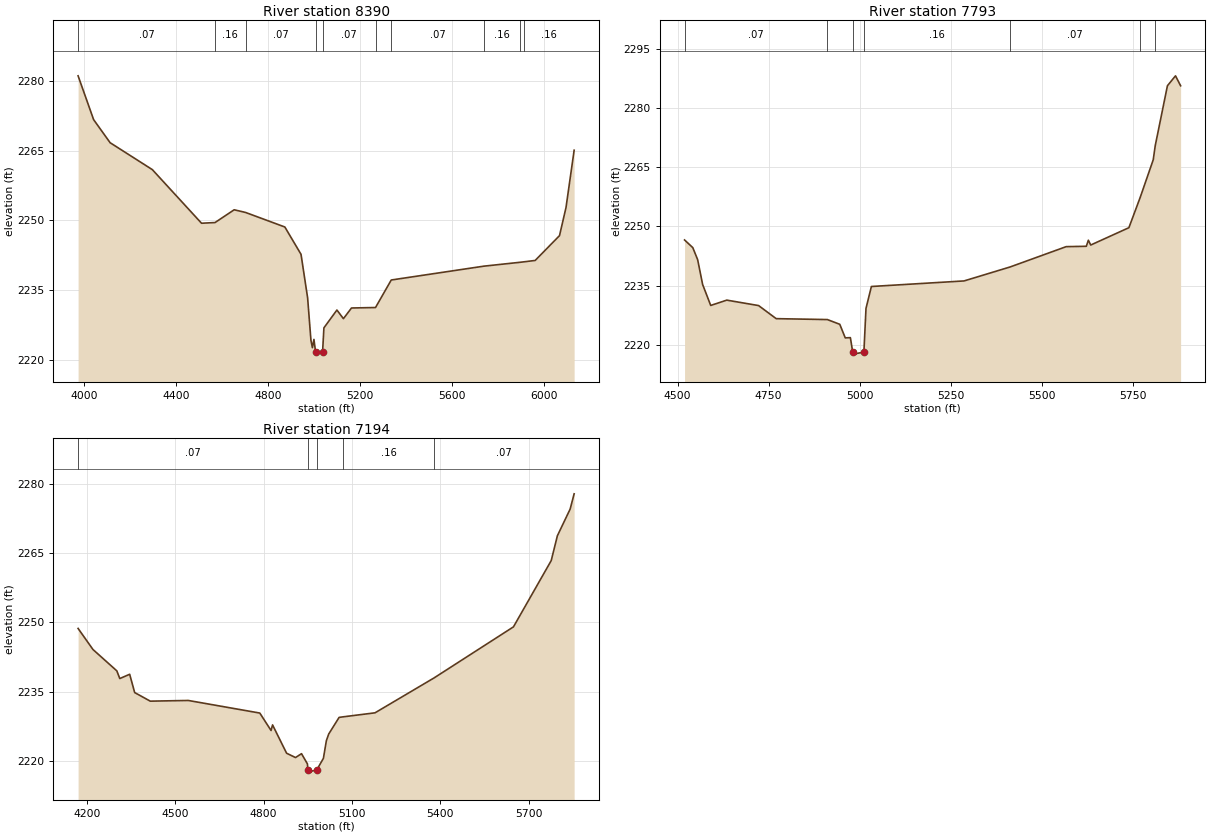
Type RM Length L Ch R = 1 ,8390    ,597,597,597
BEGIN DESCRIPTION:
Holder Creek 11.0
END DESCRIPTION:
XS GIS Cut Line= 3
      1418489.83      6819168.42      1419138.42      6818371.12
        1419955.        6817588.
#Sta/Elev= 30
  3972.2 2281.12  4039.8 2271.68  4111.6 2266.71  4295.4 2260.91  4509.5 2249.36
  4568.3 2249.51  4651.7 2252.26  4701.3 2251.68  4872.2 2248.55  4942.6 2242.66
  4971.3 2233.28  4985.7 2224.16  4992.1 2222.55  4998.8 2224.33  5005.8 2221.66
  5006.3 2221.16  5036.4 2221.66  5042.2 2226.82  5098.8 2230.66  5127.1  2228.8
  5162.3  2231.1  5266.8  2231.2  5335.3 2237.13  5738.1 2240.11  5896.8 2240.95
  5911.6 2241.04  5961.7 2241.34  6067.7 2246.69    6096 2252.75  6131.4 2265.09
#Mann= 10 ,-1 , 0
  3972.2     .07       0  4568.3     .16       0  4701.3     .07       0
  5005.8     .07       0  5036.4     .07       0  5266.8     .16       0
  5335.3     .07       0  5738.1     .16       0  5896.8     .07       0
  5911.6     .16       0
Bank Sta=5005.8,5036.4
XS Rating Curve= 0 ,0
Exp/Cntr=0.3,0.1

Type RM Length L Ch R = 1 ,7793    ,599,599,599
BEGIN DESCRIPTION:
Holder Creek 10.0
END DESCRIPTION:
XS GIS Cut Line= 3
      1419255.03      6818637.98      1419656.37       6818373.4
      1420055.01      6817587.98
#Sta/Elev= 30
  4519.3 2246.57  4541.9 2244.62  4555.2 2241.58  4568.9 2235.27  4591.1 2229.95
  4635.2  2231.3  4722.5 2229.92  4770.8  2226.6  4911.2 2226.37  4945.3 2225.17
  4960.4 2221.72  4974.4 2221.78  4980.9  2218.1  4981.4  2217.6  5011.5  2218.1
  5017.3  2229.2  5032.1 2234.76  5286.4 2236.17    5413 2239.72  5566.8 2244.87
    5622 2244.96  5627.6  2246.5  5634.1 2245.28  5738.9 2249.68  5769.9 2257.37
  5805.7 2266.92  5811.1 2270.46  5844.6 2285.69  5866.8 2288.21  5880.8 2285.69
#Mann= 7 ,-1 , 0
  4519.3     .07       0  4911.2     .16       0  4980.9     .07       0
  5011.5     .16       0    5413     .07       0  5769.9     .16       0
  5811.1     .07       0
Bank Sta=4980.9,5011.5
XS Rating Curve= 0 ,0
Exp/Cntr=0.3,0.1

Type RM Length L Ch R = 1 ,7194    ,568,568,568
BEGIN DESCRIPTION:
Holder Creek 9.0
END DESCRIPTION:
XS GIS Cut Line= 3
      1419154.99        6818738.      1419975.49       6818857.8
      1420504.99      6818188.01
#Sta/Elev= 30
  4170.8  2248.7  4221.3 2244.13  4302.2  2239.5  4312.3 2237.83  4345.8 2238.76
  4362.8 2234.79  4415.7 2232.93  4544.7 2233.08  4787.3 2230.35  4825.5 2226.57
  4830.6 2227.78  4878.2 2221.64  4908.5  2220.7  4928.8 2221.54    4949 2219.31
  4950.1 2218.04  4950.6 2217.54  4980.8 2218.04  5003.1 2220.53  5013.1 2224.35
  5021.1  2225.8  5056.4 2229.41  5068.8 2229.52  5178.2  2230.4  5378.6 2237.97
  5647.9 2249.04  5776.1 2263.42  5796.9 2268.79  5840.2 2274.58  5853.8 2277.89
#Mann= 5 ,-1 , 0
  4170.8     .07       0  4950.1     .07       0  4980.8     .07       0
  5068.8     .16       0  5378.6     .07       0
Bank Sta=4950.1,4980.8
XS Rating Curve= 0 ,0
Exp/Cntr=0.3,0.1