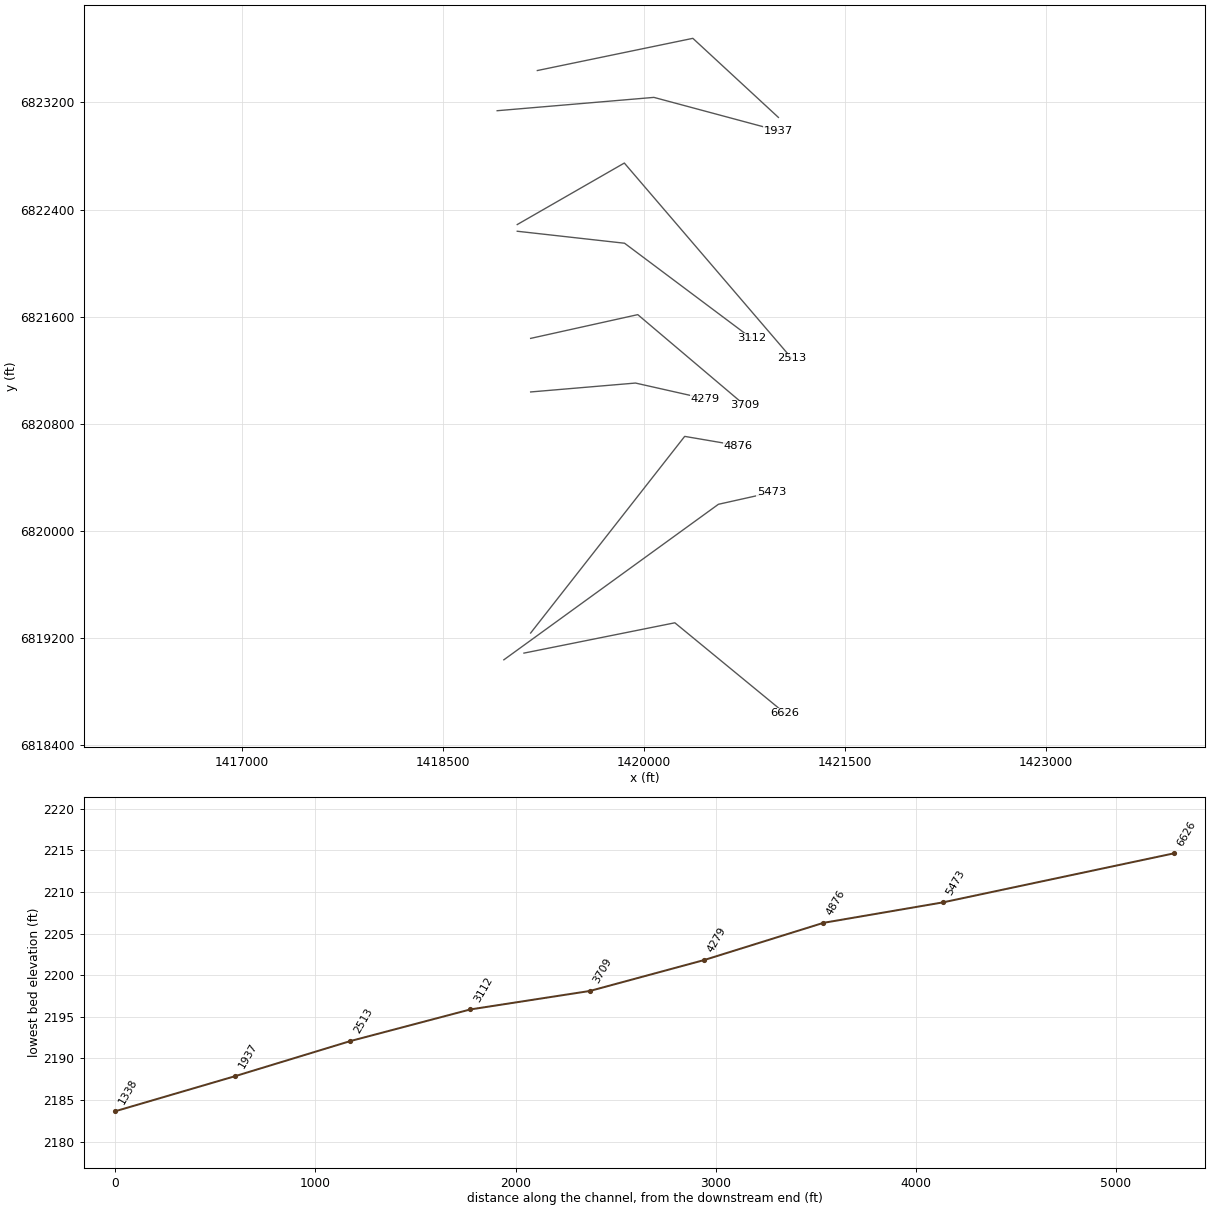
HEC-RAS study Holder Creek.prj: Holder Creek Base Level Engineering

--- Holder Creek.g01 (geometry) --- (continued)

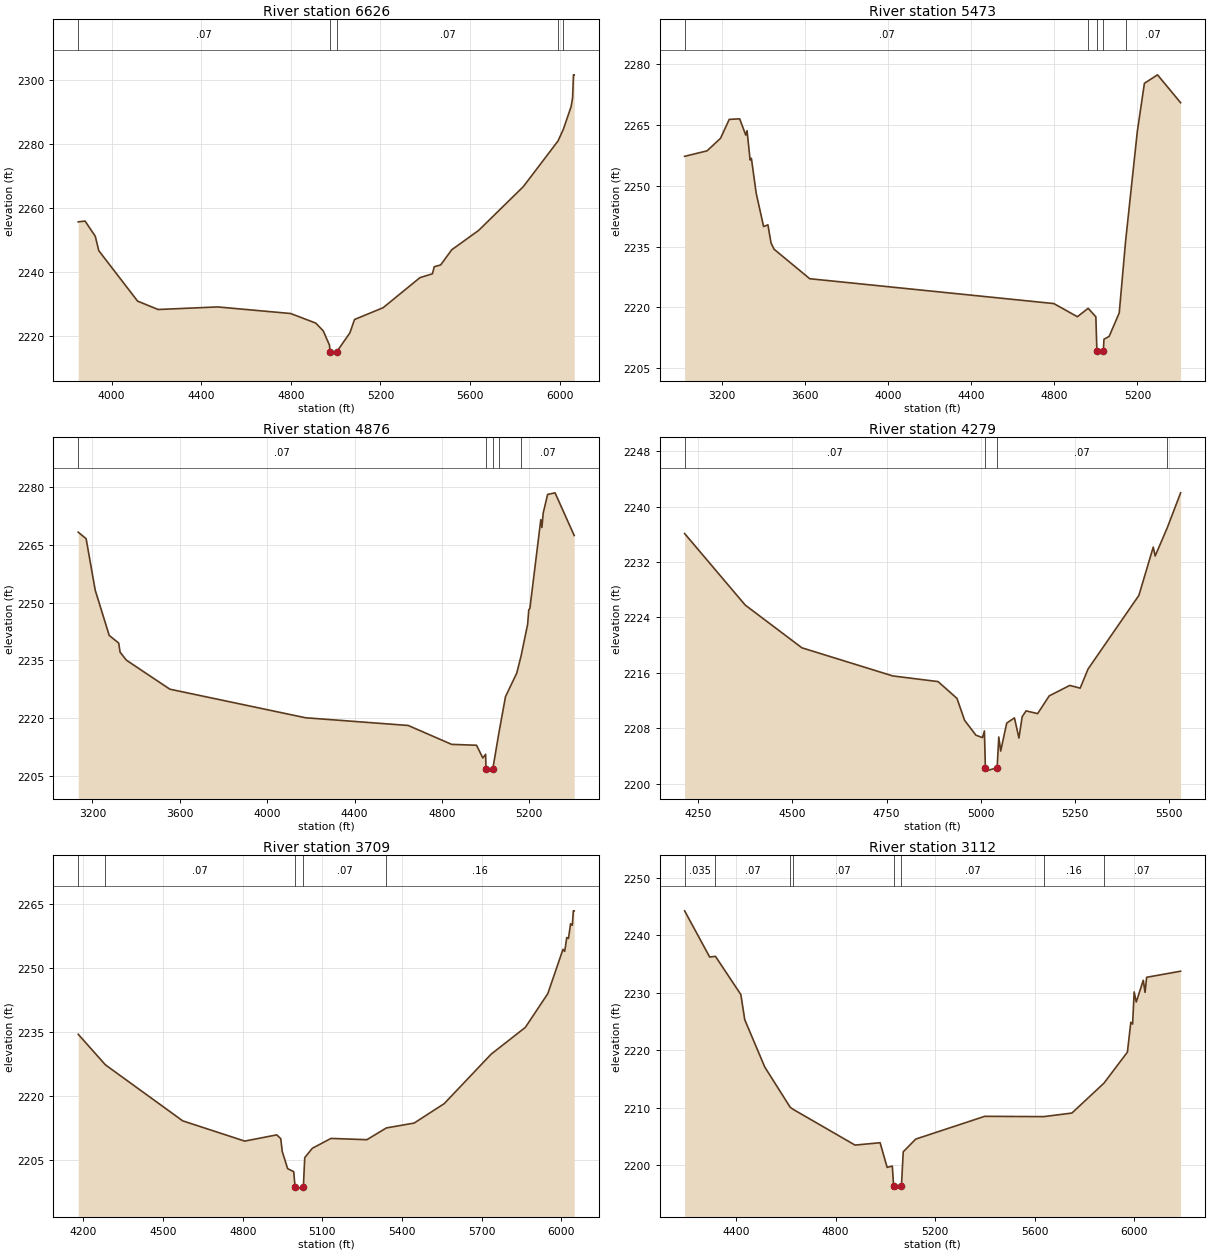
Type RM Length L Ch R = 1 ,6626    ,1153,1153,1153
BEGIN DESCRIPTION:
Holder Creek 8.0
END DESCRIPTION:
XS GIS Cut Line= 3
      1419105.02        6819088.      1420231.71      6819314.34
      1421055.01      6818637.99
#Sta/Elev= 30
  3850.8 2255.66  3881.4 2255.91  3927.1 2251.15  3942.6 2246.67    4116 2230.89
  4207.8 2228.27    4473 2229.08  4799.4 2227.02  4911.6 2224.02  4944.8 2221.61
  4972.8 2217.13  4975.3 2215.14  4975.8 2214.64    5006 2215.14  5063.8 2220.97
  5084.6 2225.15  5212.4 2228.84  5376.7 2238.23  5432.6 2239.44  5440.5 2241.64
  5469.2  2242.2  5518.7 2246.94  5638.6 2252.98    5838 2266.65  5993.2 2280.94
    6017 2284.59  6051.8 2291.71  6058.3 2294.47  6062.2 2301.61  6065.5 2301.61
#Mann= 5 ,-1 , 0
  3850.8     .07       0  4975.3     .07       0    5006     .07       0
  5993.2     .16       0    6017     .07       0
Bank Sta=4975.3,5006
XS Rating Curve= 0 ,0
Exp/Cntr=0.3,0.1

Type RM Length L Ch R = 1 ,5473    ,597,597,597
BEGIN DESCRIPTION:
Holder Creek 7.0
END DESCRIPTION:
XS GIS Cut Line= 3
      1418954.97      6819037.98      1420556.98       6820199.2
        1420955.        6820288.
#Sta/Elev= 30
  3021.4 2257.23  3129.3 2258.58  3194.3 2261.68    3236 2266.33  3286.3 2266.47
  3315.6 2262.46  3321.8 2263.55  3336.5 2256.33  3342.7 2256.73  3365.9 2248.11
  3401.5 2239.94  3422.3 2240.35    3437 2235.92  3451.7 2234.35  3623.4 2227.08
  4797.9 2220.96  4911.1 2217.72    4963 2219.79    5000  2217.7  5005.1 2209.25
  5005.6 2208.75  5035.9 2209.25    5039 2212.18    5064 2212.87  5112.5 2218.66
  5142.8 2236.19  5199.5 2263.36  5233.6 2275.22  5296.6 2277.31  5407.8 2270.44
#Mann= 5 ,-1 , 0
  3021.4     .07       0    4963     .16       0  5005.1     .07       0
  5035.9     .16       0  5142.8     .07       0
Bank Sta=5005.1,5035.9
XS Rating Curve= 0 ,0
Exp/Cntr=0.3,0.1

Type RM Length L Ch R = 1 ,4876    ,597,597,597
BEGIN DESCRIPTION:
Holder Creek 6.0
END DESCRIPTION:
XS GIS Cut Line= 3
      1419154.98      6819237.98      1420305.23      6820706.28
      1420705.04      6820637.99
#Sta/Elev= 30
  3134.8 2268.25    3171 2266.57  3212.6 2253.23  3276.8 2241.48  3320.2  2239.5
  3326.5 2237.14  3355.4 2235.06  3554.4 2227.54  4175.4 2220.13  4645.6 2218.13
  4844.5 2213.23  4958.4    2213  4987.3  2209.7    5000 2210.66  5001.8 2206.79
  5002.3 2206.29  5032.7 2206.79  5061.3 2216.37  5091.1 2225.62  5142.6 2231.72
  5162.2 2236.12  5192.5  2244.4  5197.6 2248.11  5202.7 2248.48  5252.7 2271.51
  5257.8 2269.48  5263.5 2273.19  5283.8 2278.04  5317.9 2278.46  5405.6 2267.39
#Mann= 5 ,-1 , 0
  3134.8     .07       0  5001.8     .07       0  5032.7     .07       0
  5061.3     .16       0  5162.2     .07       0
Bank Sta=5001.8,5032.7
XS Rating Curve= 0 ,0
Exp/Cntr=0.3,0.1

Type RM Length L Ch R = 1 ,4279    ,570,570,570
BEGIN DESCRIPTION:
Holder Creek 5.0
END DESCRIPTION:
XS GIS Cut Line= 3
        1419155.        6821038.      1419937.88      6821104.48
      1420455.02      6820987.99
#Sta/Elev= 30
  4214.3 2236.12  4374.9  2225.8  4525.4 2219.62  4766.3 2215.56  4886.7 2214.74
  4936.9 2212.31    4957 2209.15  4987.3 2206.99  5004.5 2206.65  5009.6 2207.61
  5012.2 2202.31  5012.7 2201.81  5043.4 2202.31  5047.7 2206.74  5052.8 2204.71
  5068.8 2208.75  5089.3  2209.5  5101.2 2206.59  5109.8 2209.67  5120.1 2210.51
  5150.8 2210.12  5181.6 2212.68  5236.1 2214.19  5263.6 2213.79  5284.5 2216.55
  5419.4 2227.19  5457.5 2234.16  5462.6 2232.88  5495.1 2237.01  5530.1    2242
#Mann= 4 ,-1 , 0
  4214.3     .07       0  5012.2     .07       0  5043.4     .07       0
  5495.1     .16       0
Bank Sta=5012.2,5043.4
XS Rating Curve= 0 ,0
Exp/Cntr=0.3,0.1

Type RM Length L Ch R = 1 ,3709    ,597,597,597
BEGIN DESCRIPTION:
Holder Creek 4.0
END DESCRIPTION:
XS GIS Cut Line= 3
      1419155.04      6821438.01      1419954.93       6821615.3
      1420755.03      6820937.98
#Sta/Elev= 30
  4180.7 2234.44    4283 2227.27  4574.2 2214.12  4807.5 2209.37  4928.4 2210.83
  4943.4 2209.93  4948.9 2206.95  4969.3  2202.9  4992.2  2202.2  4997.2  2198.6
  4997.7  2198.1  5028.4  2198.6  5033.7 2205.49  5062.3 2207.69  5132.5    2210
  5267.7  2209.7  5341.1 2212.46  5445.6  2213.6  5558.8 2218.16  5735.7 2229.78
  5864.3 2236.05  5948.8 2243.96    6006 2254.36  6012.5 2253.89  6020.3 2257.13
  6026.8 2256.93  6034.6 2260.36  6041.1 2260.01    6045  2263.4  6048.3  2263.4
#Mann= 5 ,-1 , 0
  4180.7    .035       0    4283     .07       0  4997.2     .07       0
  5028.4     .07       0  5341.1     .16       0
Bank Sta=4997.2,5028.4
XS Rating Curve= 0 ,0
Exp/Cntr=0.3,0.1

Type RM Length L Ch R = 1 ,3112    ,599,599,599
BEGIN DESCRIPTION:
Holder Creek 3.0
END DESCRIPTION:
XS GIS Cut Line= 3
        1419055.        6822238.      1419856.22       6822148.5
      1420804.98      6821438.02
#Sta/Elev= 30
  4193.8 2244.28  4294.4 2236.25  4317.7 2236.36  4419.6 2229.72  4435.3 2225.34
  4515.8  2217.1  4617.7 2210.12  4627.8  2209.8    4878 2203.54  4978.7 2203.95
    5007 2199.66  5027.8 2199.89    5033 2196.38  5033.5 2195.88  5064.3 2196.38
  5071.6 2202.37  5121.6 2204.58  5398.7 2208.54  5635.4 2208.49  5748.8 2209.11
  5877.7 2214.32  5971.7 2219.71  5985.4  2224.9  5992.6 2224.59  5998.8 2230.18
  6007.2 2228.42  6035.4  2232.2  6042.6 2230.09  6048.8 2232.72  6185.3 2233.78
#Mann= 8 ,-1 , 0
  4193.8    .035       0  4317.7     .07       0  4617.7    .035       0
  4627.8     .07       0    5033     .07       0  5064.3     .07       0
  5635.4     .16       0  5877.7     .07       0
Bank Sta=5033,5064.3
XS Rating Curve= 0 ,0
Exp/Cntr=0.3,0.1

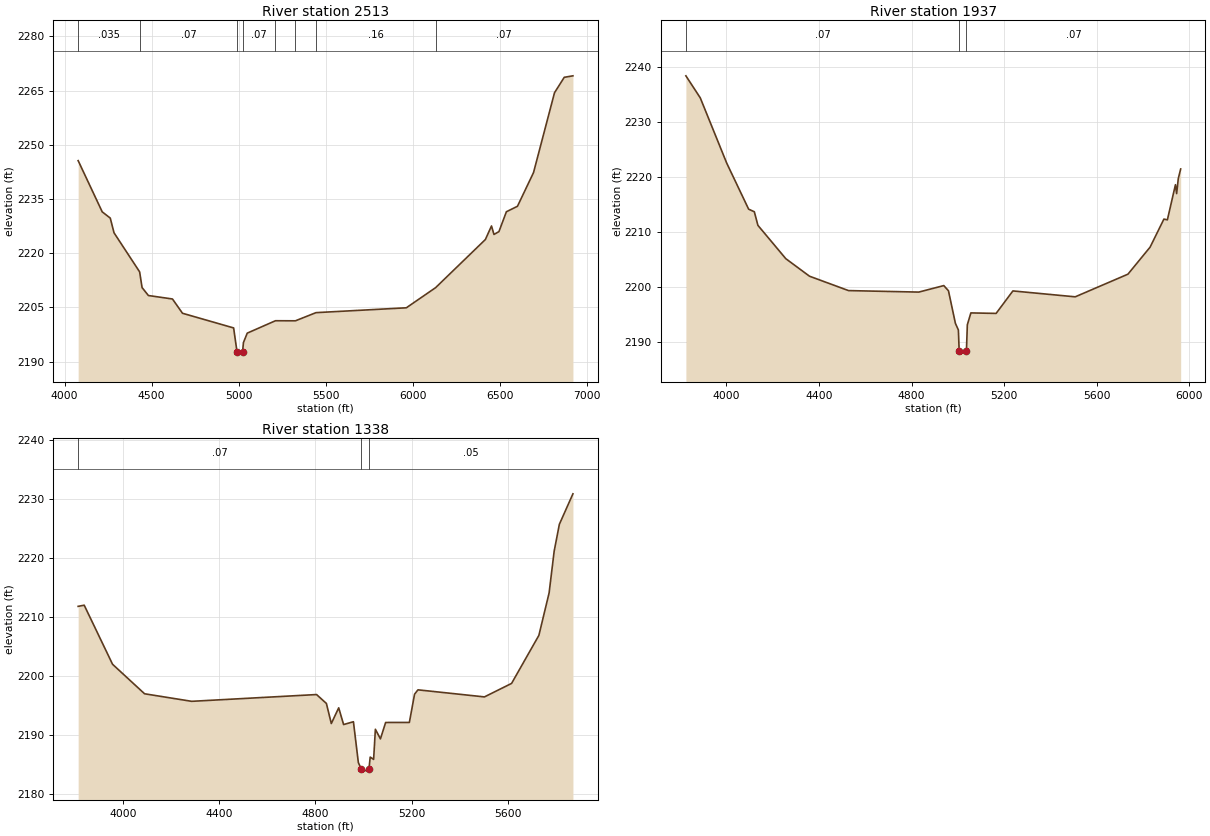
Type RM Length L Ch R = 1 ,2513    ,576,576,576
BEGIN DESCRIPTION:
Holder Creek 2.0
END DESCRIPTION:
XS GIS Cut Line= 3
      1419054.98      6822287.99      1419854.55      6822747.28
      1421104.97      6821288.04
#Sta/Elev= 30
  4077.9 2245.63  4216.3 2231.45  4262.4 2229.73  4284.2 2225.65  4431.2 2214.85
  4445.3  2210.5  4481.6  2208.3    4620 2207.34  4677.6 2203.39  4971.5 2199.33
  4991.4 2192.58  4991.9 2192.08  5022.7 2192.58  5027.9 2195.28  5049.8 2197.89
    5212 2201.32  5326.7  2201.3  5444.9 2203.56  5964.1  2204.9  6132.5 2210.48
  6418.5  2223.8  6453.6 2227.55  6467.9  2225.2  6496.4 2225.99  6539.2 2231.48
  6602.9    2233  6695.1 2242.31  6815.8 2264.42  6871.8 2268.69  6921.7  2269.1
#Mann= 8 ,-1 , 0
  4077.9    .035       0  4431.2     .07       0  4991.4     .07       0
  5022.7     .07       0    5212     .16       0  5326.7     .07       0
  5444.9     .16       0  6132.5     .07       0
Bank Sta=4991.4,5022.7
XS Rating Curve= 0 ,0
Exp/Cntr=0.3,0.1

Type RM Length L Ch R = 1 ,1937    ,599,599,599
BEGIN DESCRIPTION:
Holder Creek 1.0
END DESCRIPTION:
XS GIS Cut Line= 3
      1418904.99        6823138.      1420075.37      6823237.52
      1421004.97      6822988.01
#Sta/Elev= 30
  3825.4 2238.37  3887.5 2234.37  4001.7 2222.53  4096.4 2214.17    4121  2213.7
  4136.5 2211.23    4257 2205.18  4359.4    2202  4527.9 2199.39  4831.3 2199.12
  4939.4  2200.3  4959.5 2199.36  4989.6 2193.43  5002.4 2192.24  5005.8 2188.36
  5006.3 2187.86  5037.1 2188.36    5041 2193.18  5056.3 2195.34  5165.3 2195.25
  5237.8 2199.33    5507 2198.26  5734.7 2202.37  5830.3 2207.27  5890.1 2212.37
  5905.1 2212.23  5939.9 2218.61  5945.1 2216.99  5952.2 2219.73  5962.5 2221.46
#Mann= 3 ,-1 , 0
  3825.4     .07       0  5005.8     .07       0  5037.1     .07       0
Bank Sta=5005.8,5037.1
XS Rating Curve= 0 ,0
Exp/Cntr=0.3,0.1

Type RM Length L Ch R = 1 ,1338    ,0,0,0
BEGIN DESCRIPTION:
Holder Creek 0.1
END DESCRIPTION:
XS GIS Cut Line= 3
      1419205.03      6823438.01       1420366.2      6823678.45
      1421005.01      6823087.99
#Sta/Elev= 30
  3814.2 2211.76  3839.3 2211.96  3957.1 2201.94  4090.2 2196.93  4285.9 2195.65
  4804.7  2196.8  4845.6 2195.29    4866 2191.88  4896.7 2194.55  4917.1 2191.71
  4957.9 2192.19  4978.4 2185.25    4991 2184.14  4991.5 2183.64  5022.3 2184.14
  5027.6 2186.19  5041.8  2185.8  5049.1 2190.91  5070.1 2189.28  5091.7 2192.06
  5190.3 2192.07  5211.9 2196.86    5226  2197.6  5502.2  2196.4    5615 2198.69
  5728.4 2206.84  5770.9 2214.04  5791.9 2221.12  5813.5 2225.68  5869.9 2230.85
#Mann= 3 ,-1 , 0
  3814.2     .07       0    4991     .05       0  5022.3     .05       0
Bank Sta=4991,5022.3
XS Rating Curve= 0 ,0
Exp/Cntr=0.3,0.1

Chan Stop Cuts=-1
Use User Specified Reach Order=0
Composite Channel Slope=5