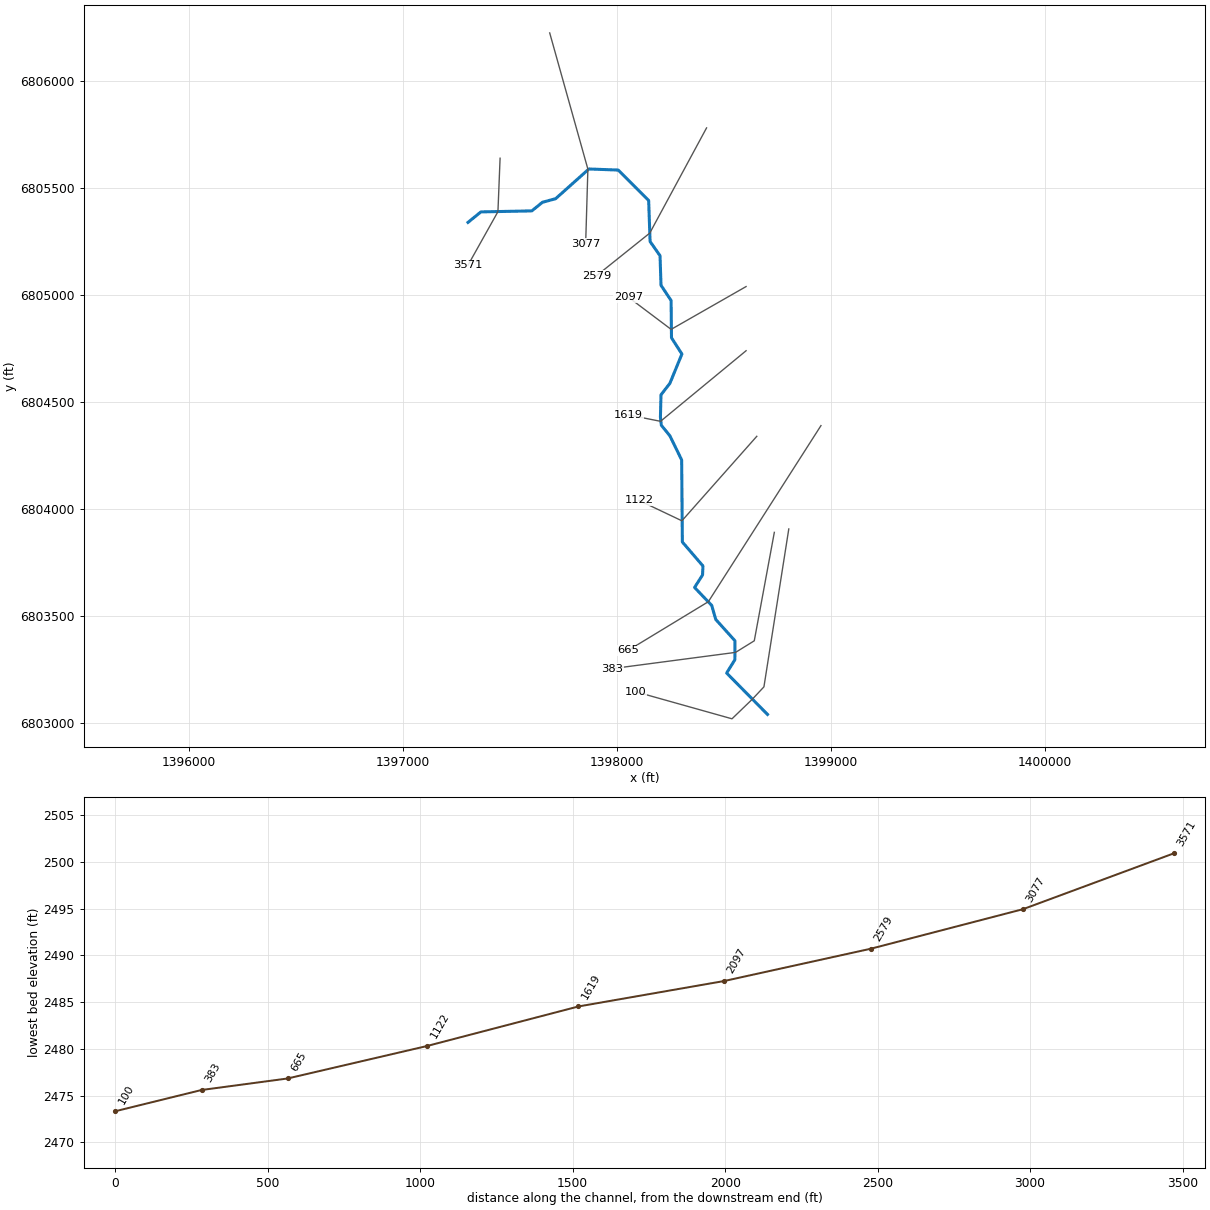
--- Holder Creek Trib1.prj (project) ---

Proj Title=Holder Creek Trib1 Base Level Engineering
Current Plan=p01
Default Exp/Contr=0.3,0.1
English Units
Geom File=g01
Flow File=f01
Plan File=p01
Y Axis Title=Elevation
X Axis Title(PF)=Main Channel Distance
X Axis Title(XS)=Station
BEGIN DESCRIPTION:
Holder Creek Trib1
END DESCRIPTION:
DSS Export Rating Curves= 0
DSS Export Rating Curve Sorted= 0
DSS Export Volume Flow Curves= 0
DXF OffsetX= 0
DXF OffsetY= 0
DXF ScaleX= 1
DXF ScaleY= 10

--- Holder Creek Trib1.p01 (plan) ---

Plan Title=Multiple Run
Short Identifier=Multiple
Geom File=g01
Flow File=f01
Subcritical Flow
K Sum by GR= 0
Std Step Tol= 0.01
Critical Tol= 0.01
Num of Std Step Trials= 20
Max Error Tol= 0.3
Flow Tol Ratio= 0.001
Split Flow NTrial= 30
Split Flow Tol= 0.02
Split Flow Ratio= 0.02
Log Output Level= 0
Friction Slope Method= 1
Unsteady Friction Slope Method= 2
Unsteady Bridges Friction Slope Method= 1
Parabolic Critical Depth
Global Vel Dist=  1 , 1 , 1
Global Log Level= 0
CheckData=True
Encroach Param= -1, 0, 0, 0
BEGIN DESCRIPTION:
Multiple Run
END DESCRIPTION:

--- Holder Creek Trib1.f01 (steady flow) ---

Flow Title=Multiple
Program Version=4.10
Number of Profiles= 7
Profile Names=10-year,25-year,50-year,1pct_min,100-year,1pct_plu,500-year
River Rch & RM=Holder Creek Tri,Reach-1         ,3571
     278     392     488     302     603    1204     933
River Rch & RM=Holder Creek Tri,Reach-1         ,2579
     349     499     626     391     779    1555    1222
Boundary for River Rch & Prof#=Holder Creek Tri,Reach-1         , 1
Up Type= 0
Dn Type= 3
Dn Slope=0.008
Boundary for River Rch & Prof#=Holder Creek Tri,Reach-1         , 2
Up Type= 0
Dn Type= 3
Dn Slope=0.008
Boundary for River Rch & Prof#=Holder Creek Tri,Reach-1         , 3
Up Type= 0
Dn Type= 3
Dn Slope=0.008
Boundary for River Rch & Prof#=Holder Creek Tri,Reach-1         , 4
Up Type= 0
Dn Type= 3
Dn Slope=0.008
Boundary for River Rch & Prof#=Holder Creek Tri,Reach-1         , 5
Up Type= 0
Dn Type= 3
Dn Slope=0.008
Boundary for River Rch & Prof#=Holder Creek Tri,Reach-1         , 6
Up Type= 0
Dn Type= 3
Dn Slope=0.008
Boundary for River Rch & Prof#=Holder Creek Tri,Reach-1         , 7
Up Type= 0
Dn Type= 3
Dn Slope=0.008
DSS Import GetInterval= 0
DSS Import GetPeak= 0
DSS Import FillOption= 0

--- Holder Creek Trib1.g01 (geometry) ---

Geom Title=Existing Conditions

River Reach=Holder Creek Tri,Reach-1
Reach XY= 30
      1397305.00      6805338.00      1397365.40      6805387.04
      1397603.45      6805391.75      1397652.83      6805431.86
      1397714.68      6805448.76      1397870.16      6805587.64
      1398007.45      6805582.55      1398149.54      6805440.45
      1398156.22      6805248.51      1398202.73      6805182.06
      1398207.27      6805043.94      1398254.48      6804972.78
      1398256.24      6804798.50      1398304.91      6804722.60
      1398248.89      6804585.82      1398207.23      6804532.07
      1398204.50      6804427.83      1398208.74      6804389.56
      1398248.88      6804340.18      1398303.80      6804227.50
      1398307.07      6803843.86      1398403.33      6803731.95
      1398401.41      6803689.65      1398364.17      6803631.28
      1398444.17      6803547.68      1398463.18      6803481.96
      1398553.02      6803382.10      1398552.63      6803293.89
      1398514.13      6803231.26      1398705.00      6803038.00

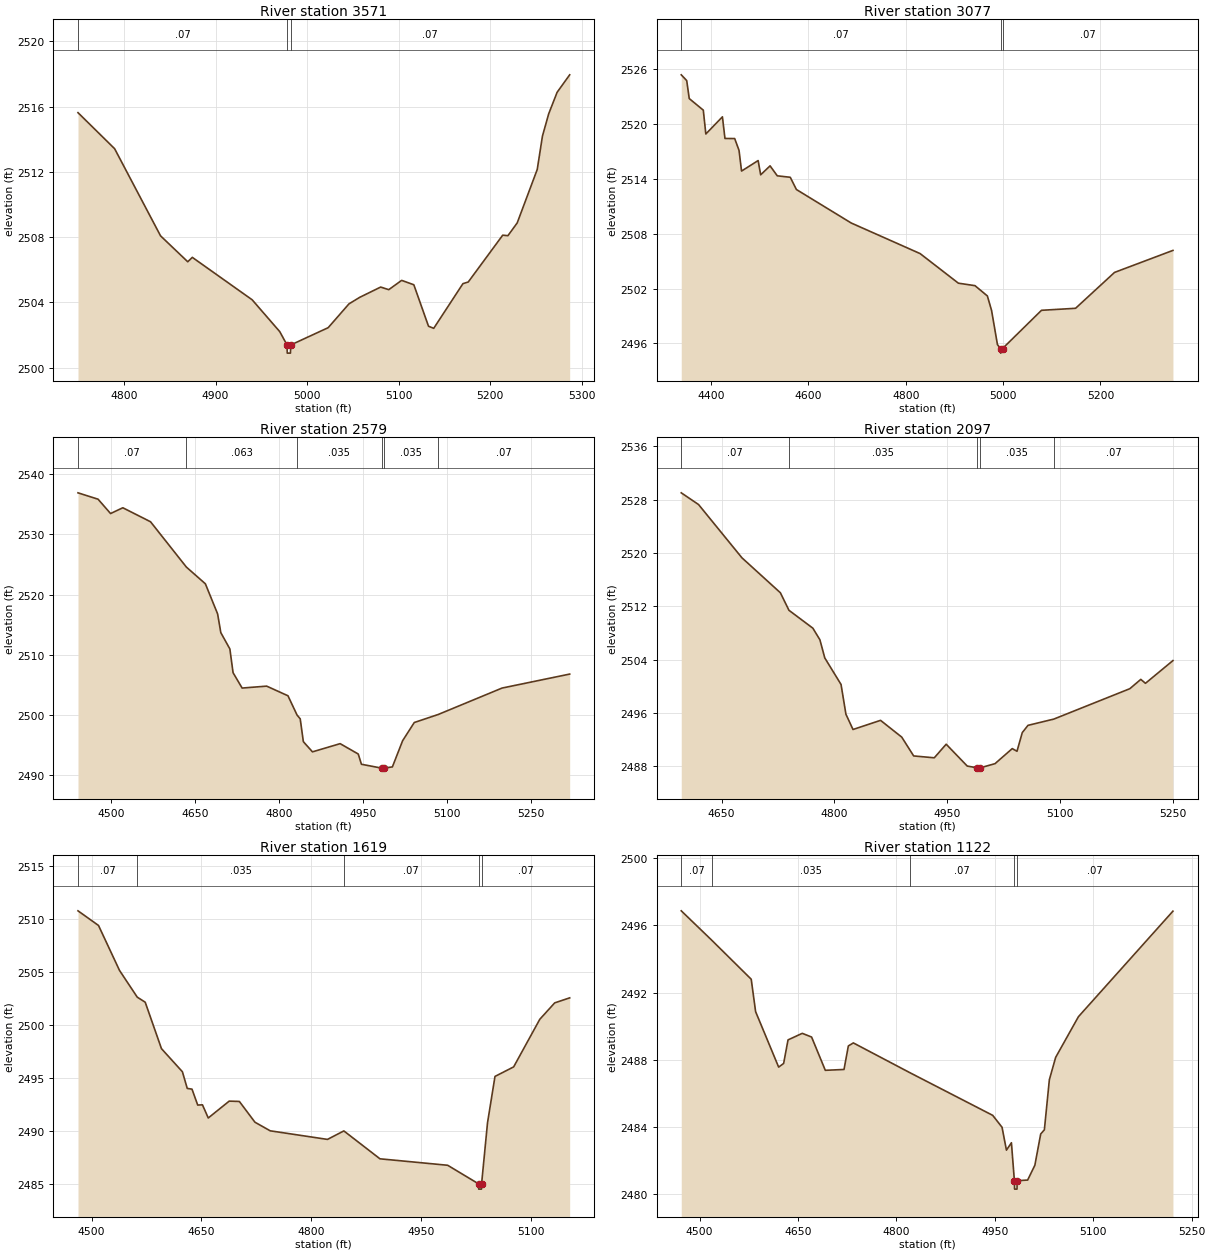
Type RM Length L Ch R = 1,3571,494,494,494
BEGIN DESCRIPTION:
Holder Creek Trib1 6.0
END DESCRIPTION:
XS GIS Cut Line= 3
      1397455.00      6805637.99      1397444.96      6805388.10
      1397305.00      6805138.00
#Sta/Elev= 30
  4749.9 2515.63  4789.9 2513.42  4840.0 2508.08  4869.7 2506.49  4874.7 2506.76
  4940.0 2504.16  4970.1 2502.21  4978.1 2501.39  4978.3 2500.89  4981.8 2500.89
  4982.1 2501.39  5023.0 2502.45  5045.7 2503.91  5057.4 2504.31  5080.3 2504.94
  5089.1 2504.78  5103.2 2505.35  5116.5 2505.08  5132.5 2502.54  5138.2 2502.41
  5170.1 2505.15  5175.9 2505.25  5213.5 2508.12  5219.2 2508.09  5229.3 2508.87
  5251.2 2512.15  5256.9 2514.20  5263.7 2515.56  5272.9 2516.88  5286.6 2517.95
#Mann=3,-1,0
  4749.9    0.07       0  4978.1    0.07       0  4982.1    0.07       0
Bank Sta=4978.1,4982.1
Exp/Cntr=0.3,0.1

Type RM Length L Ch R = 1,3077,498,498,498
BEGIN DESCRIPTION:
Holder Creek Trib1 5.0
END DESCRIPTION:
XS GIS Cut Line= 3
      1397686.93      6806223.72      1397865.44      6805586.97
      1397855.00      6805238.02
#Sta/Elev= 30
  4338.7 2525.41  4349.9 2524.78  4355.1 2522.81  4384.0 2521.54  4389.2 2518.93
  4423.3 2520.81  4428.5 2518.44  4448.5 2518.43  4457.4 2517.14  4462.6 2514.87
  4496.7 2516.02  4501.9 2514.46  4521.2 2515.44  4536.0 2514.35  4562.7 2514.19
  4575.3 2512.85  4688.0 2509.18  4829.6 2505.83  4908.2 2502.59  4942.3 2502.32
  4967.8 2501.19  4976.4 2499.60  4988.5 2495.86  4994.9 2495.43  4995.1 2494.93
  4998.9 2495.43  5079.0 2499.62  5149.0 2499.84  5229.1 2503.77  5349.1 2506.18
#Mann=3,-1,0
  4338.7    0.07       0  4994.9    0.07       0  4998.9    0.07       0
Bank Sta=4994.9,4998.9
Exp/Cntr=0.3,0.1

Type RM Length L Ch R = 1,2579,482,482,482
BEGIN DESCRIPTION:
Holder Creek Trib1 4.0
END DESCRIPTION:
XS GIS Cut Line= 3
      1398420.16      6805779.61      1398154.60      6805287.83
      1397905.03      6805088.03
#Sta/Elev= 30
  4441.1 2536.91  4477.0 2535.85  4499.3 2533.47  4521.2 2534.43  4570.7 2532.11
  4634.8 2524.58  4668.7 2521.81  4690.6 2516.81  4696.3 2513.70  4712.5 2510.99
  4718.2 2507.05  4734.4 2504.50  4778.2 2504.82  4816.3 2503.22  4832.6 2500.01
  4838.2 2499.39  4843.8 2495.60  4860.1 2493.91  4909.5 2495.27  4941.9 2493.55
  4947.6 2491.85  4983.6 2491.21  4983.9 2490.71  4987.7 2491.21  5002.9 2491.41
  5021.2 2495.76  5042.0 2498.78  5085.0 2500.12  5198.9 2504.50  5319.7 2506.82
#Mann=6,-1,0
  4441.1    0.07       0  4634.8   0.063       0  4832.6   0.035       0
  4983.6   0.035       0  4987.7   0.035       0  5085.0    0.07       0
Bank Sta=4983.6,4987.7
Exp/Cntr=0.3,0.1

Type RM Length L Ch R = 1,2097,478,478,478
BEGIN DESCRIPTION:
Holder Creek Trib1 3.0
END DESCRIPTION:
XS GIS Cut Line= 3
      1398604.96      6805037.98      1398254.60      6804837.83
      1398054.99      6804988.01
#Sta/Elev= 30
  4596.5 2529.02  4619.5 2527.26  4677.1 2519.27  4728.2 2514.02  4739.6 2511.39
  4771.4 2508.70  4780.7 2506.97  4787.2 2504.24  4808.8 2500.26  4815.3 2495.79
  4824.7 2493.50  4861.3 2494.87  4889.5 2492.35  4905.3 2489.53  4932.7 2489.25
  4948.5 2491.29  4976.5 2488.01  4989.6 2487.75  4989.9 2487.25  4993.8 2487.75
  5013.4 2488.37  5036.3 2490.63  5042.6 2490.23  5049.6 2493.03  5057.2 2494.12
  5091.5 2495.06  5192.5 2499.62  5207.1 2501.02  5213.3 2500.43  5249.8 2503.84
#Mann=5,-1,0
  4596.5    0.07       0  4739.6   0.035       0  4989.6   0.035       0
  4993.8   0.035       0  5091.5    0.07       0
Bank Sta=4989.6,4993.8
Exp/Cntr=0.3,0.1

Type RM Length L Ch R = 1,1619,497,497,497
BEGIN DESCRIPTION:
Holder Creek Trib1 2.0
END DESCRIPTION:
XS GIS Cut Line= 3
      1398605.00      6804738.00      1398205.04      6804408.03
      1398055.00      6804438.00
#Sta/Elev= 30
  4481.5 2510.78  4509.5 2509.40  4538.2 2505.16  4562.4 2502.64  4573.3 2502.16
  4595.5 2497.78  4624.1 2495.60  4630.7 2494.03  4637.2 2493.96  4645.0 2492.46
  4651.5 2492.48  4659.4 2491.24  4688.0 2492.83  4701.9 2492.80  4723.2 2490.84
  4744.0 2490.03  4822.2 2489.22  4844.6 2490.02  4893.9 2487.39  4986.4 2486.78
  5028.5 2485.03  5028.8 2484.53  5032.5 2484.53  5032.7 2485.03  5040.8 2490.79
  5051.0 2495.16  5076.5 2496.06  5112.2 2500.55  5132.6 2502.10  5153.0 2502.57
#Mann=5,-1,0
  4481.5    0.07       0  4562.4   0.035       0  4844.6    0.07       0
  5028.5    0.07       0  5032.7    0.07       0
Bank Sta=5028.5,5032.7
Exp/Cntr=0.3,0.1

Type RM Length L Ch R = 1,1122,457,457,457
BEGIN DESCRIPTION:
Holder Creek Trib1 1.0
END DESCRIPTION:
XS GIS Cut Line= 3
      1398654.99      6804337.99      1398304.94      6803942.97
      1398104.97      6804038.01
#Sta/Elev= 30
  4472.2 2496.86  4518.7 2495.11  4578.8 2492.79  4585.5 2490.86  4620.6 2487.56
  4628.2 2487.78  4634.9 2489.18  4656.6 2489.57  4670.8 2489.35  4691.7 2487.37
  4720.2 2487.42  4726.8 2488.82  4734.4 2489.00  4820.0 2487.24  4946.8 2484.69
  4961.0 2483.98  4967.7 2482.62  4975.3 2483.06  4979.8 2480.80  4980.1 2480.30
  4983.8 2480.30  4984.1 2480.80  5000.0 2480.84  5011.0 2481.72  5019.9 2483.58
  5025.5 2483.83  5033.1 2486.81  5042.7 2488.14  5077.4 2490.56  5221.4 2496.84
#Mann=5,-1,0
  4472.2    0.07       0  4518.7   0.035       0  4820.0    0.07       0
  4979.8    0.07       0  4984.1    0.07       0
Bank Sta=4979.8,4984.1
Exp/Cntr=0.3,0.1

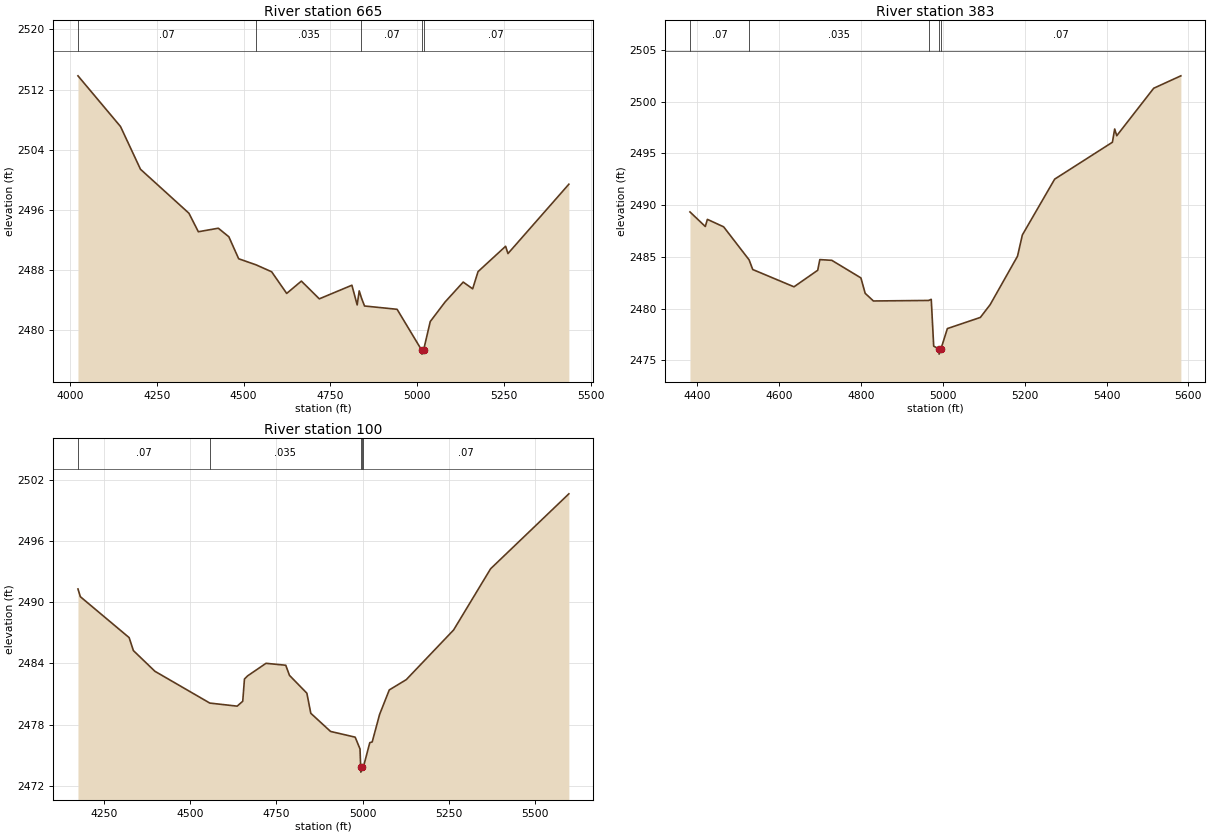
Type RM Length L Ch R = 1,665,282,282,282
BEGIN DESCRIPTION:
Holder Creek Trib1 2584
END DESCRIPTION:
XS GIS Cut Line= 3
      1398954.99      6804387.99      1398428.57      6803564.82
      1398055.03      6803338.02
#Sta/Elev= 30
  4022.9 2513.83  4145.5 2507.09  4203.0 2501.41  4342.6 2495.56  4369.7 2493.10
  4427.2 2493.57  4457.6 2492.43  4485.8 2489.51  4536.5 2488.69  4580.8 2487.78
  4624.2 2484.90  4666.5 2486.54  4718.1 2484.18  4812.0 2485.99  4827.2 2483.37
  4833.1 2485.24  4839.6 2484.29  4848.4 2483.23  4942.2 2482.79  5013.4 2477.33
  5013.8 2476.83  5018.3 2477.33  5037.7 2481.16  5080.4 2483.76  5132.7 2486.41
  5159.9 2485.51  5175.4 2487.80  5254.8 2491.17  5261.6 2490.20  5437.0 2499.42
#Mann=5,-1,0
  4022.9    0.07       0  4536.5   0.035       0  4839.6    0.07       0
  5013.4    0.07       0  5018.3    0.07       0
Bank Sta=5013.4,5018.3
Exp/Cntr=0.3,0.1

Type RM Length L Ch R = 1,383,283,283,283
BEGIN DESCRIPTION:
Holder Creek Trib1 4464
END DESCRIPTION:
XS GIS Cut Line= 4
      1398736.99      6803888.96      1398643.24      6803382.02
      1398555.74      6803327.93      1397979.13      6803251.92
#Sta/Elev= 30
  4381.6 2489.35  4419.1 2487.94  4424.2 2488.63  4463.9 2487.91  4526.1 2484.72
  4535.1 2483.78  4635.9 2482.11  4693.9 2483.71  4699.0 2484.74  4728.3 2484.67
  4799.5 2482.97  4809.9 2481.48  4830.0 2480.74  4965.1 2480.79  4971.4 2480.90
  4977.4 2476.37  4990.2 2476.10  4990.6 2475.60  4995.1 2476.10  5010.8 2478.07
  5091.5 2479.15  5115.5 2480.39  5182.3 2485.07  5194.1 2487.12  5273.1 2492.52
  5414.3 2496.09  5419.8 2497.37  5424.9 2496.72  5515.2 2501.31  5581.6 2502.51
#Mann=5,-1,0
  4381.6    0.07       0  4526.1   0.035       0  4965.1    0.07       0
  4990.2    0.07       0  4995.1    0.07       0
Bank Sta=4990.2,4995.1
Exp/Cntr=0.3,0.1

Type RM Length L Ch R = 1,100,0,0,0
BEGIN DESCRIPTION:
Holder Creek Trib1 4463
END DESCRIPTION:
XS GIS Cut Line= 5
      1398804.60      6803904.89      1398688.38      6803166.74
      1398634.03      6803108.92      1398539.08      6803017.43
      1398088.84      6803143.84
#Sta/Elev= 30
  4173.4 2491.29  4180.4 2490.53  4322.1 2486.52  4334.4 2485.25  4396.9 2483.22
  4556.5 2480.10  4635.9 2479.80  4652.1 2480.28  4657.1 2482.46  4666.3 2482.77
  4719.7 2484.00  4777.1 2483.81  4787.8 2482.82  4838.4 2481.07  4849.8 2479.10
  4907.2 2477.32  4978.7 2476.76  4992.8 2475.60  4994.7 2473.83  4995.1 2473.33
  4999.6 2473.83  5002.6 2473.83  5021.2 2476.22  5028.2 2476.29  5049.5 2478.97
  5077.8 2481.39  5127.2 2482.40  5264.7 2487.27  5372.1 2493.27  5599.5 2500.62
#Mann=5,-1,0
  4173.4    0.07       0  4556.5   0.035       0  4994.7   0.035       0
  4999.6   0.035       0  5002.6    0.07       0
Bank Sta=4994.7,4999.6
Exp/Cntr=0.3,0.1

Chan Stop Cuts=-1