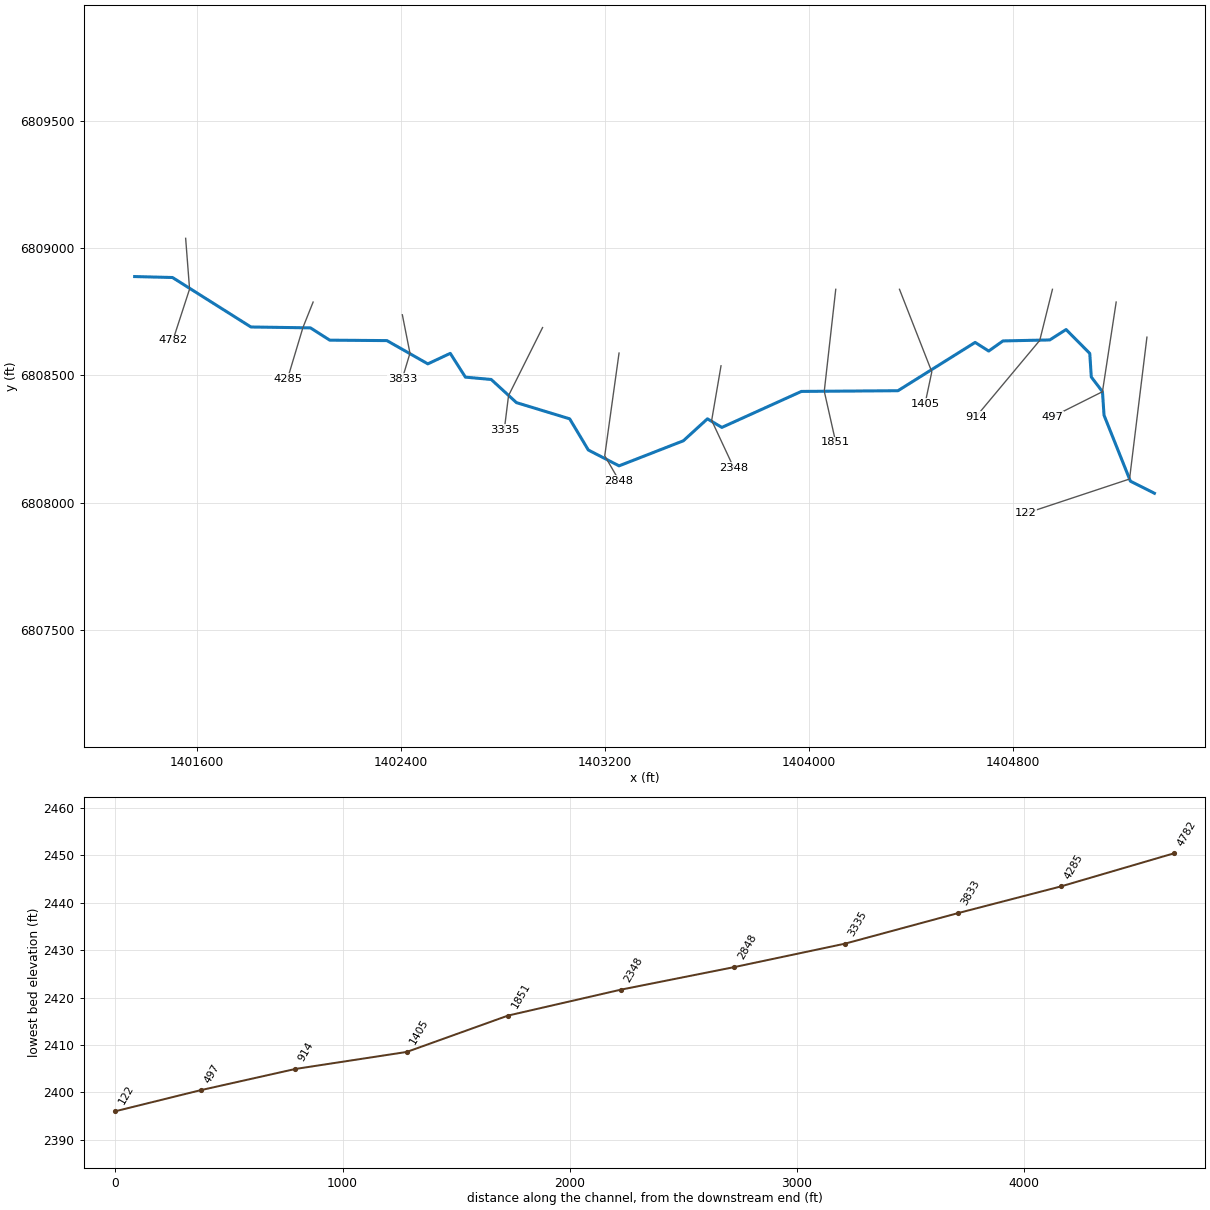
--- Holder Creek Trib2.prj (project) ---

Proj Title=Holder Creek Trib2 Base Level Engineering
Current Plan=p01
Default Exp/Contr=0.3,0.1
English Units
Geom File=g01
Flow File=f01
Plan File=p01
Y Axis Title=Elevation
X Axis Title(PF)=Main Channel Distance
X Axis Title(XS)=Station
BEGIN DESCRIPTION:
Holder Creek Trib2
END DESCRIPTION:
DSS Export Rating Curves= 0
DSS Export Rating Curve Sorted= 0
DSS Export Volume Flow Curves= 0
DXF OffsetX= 0
DXF OffsetY= 0
DXF ScaleX= 1
DXF ScaleY= 10

--- Holder Creek Trib2.p01 (plan) ---

Plan Title=Multiple Run
Short Identifier=Multiple
Geom File=g01
Flow File=f01
Subcritical Flow
K Sum by GR= 0
Std Step Tol= 0.01
Critical Tol= 0.01
Num of Std Step Trials= 20
Max Error Tol= 0.3
Flow Tol Ratio= 0.001
Split Flow NTrial= 30
Split Flow Tol= 0.02
Split Flow Ratio= 0.02
Log Output Level= 0
Friction Slope Method= 1
Unsteady Friction Slope Method= 2
Unsteady Bridges Friction Slope Method= 1
Parabolic Critical Depth
Global Vel Dist=  1 , 1 , 1
Global Log Level= 0
CheckData=True
Encroach Param= -1, 0, 0, 0
BEGIN DESCRIPTION:
Multiple Run
END DESCRIPTION:

--- Holder Creek Trib2.f01 (steady flow) ---

Flow Title=Multiple
Program Version=4.10
Number of Profiles= 7
Profile Names=10-year,25-year,50-year,1pct_min,100-year,1pct_plu,500-year
River Rch & RM=Holder Creek Tri,Reach-1         ,4782
     489     716     913     578    1154    2303    1869
Boundary for River Rch & Prof#=Holder Creek Tri,Reach-1         , 1
Up Type= 0
Dn Type= 3
Dn Slope=0.012
Boundary for River Rch & Prof#=Holder Creek Tri,Reach-1         , 2
Up Type= 0
Dn Type= 3
Dn Slope=0.012
Boundary for River Rch & Prof#=Holder Creek Tri,Reach-1         , 3
Up Type= 0
Dn Type= 3
Dn Slope=0.012
Boundary for River Rch & Prof#=Holder Creek Tri,Reach-1         , 4
Up Type= 0
Dn Type= 3
Dn Slope=0.012
Boundary for River Rch & Prof#=Holder Creek Tri,Reach-1         , 5
Up Type= 0
Dn Type= 3
Dn Slope=0.012
Boundary for River Rch & Prof#=Holder Creek Tri,Reach-1         , 6
Up Type= 0
Dn Type= 3
Dn Slope=0.012
Boundary for River Rch & Prof#=Holder Creek Tri,Reach-1         , 7
Up Type= 0
Dn Type= 3
Dn Slope=0.012
DSS Import GetInterval= 0
DSS Import GetPeak= 0
DSS Import FillOption= 0

--- Holder Creek Trib2.g01 (geometry) ---

Geom Title=Existing Conditions

River Reach=Holder Creek Tri,Reach-1
Reach XY= 30
      1401355.00      6808888.00      1401503.46      6808884.28
      1401810.93      6808690.24      1402044.50      6808686.78
      1402120.22      6808638.52      1402344.50      6808636.80
      1402505.03      6808545.57      1402592.96      6808586.76
      1402652.34      6808493.46      1402753.50      6808484.37
      1402852.58      6808393.54      1403061.34      6808329.98
      1403134.53      6808207.62      1403254.99      6808145.53
      1403507.30      6808243.86      1403601.67      6808329.99
      1403658.23      6808296.25      1403970.22      6808437.48
      1404349.07      6808440.24      1404651.77      6808629.76
      1404704.90      6808595.80      1404760.85      6808635.55
      1404944.57      6808639.39      1405008.43      6808680.21
      1405101.39      6808586.53      1405107.36      6808493.98
      1405151.15      6808436.40      1405157.35      6808343.97
      1405260.68      6808085.48      1405355.00      6808038.00

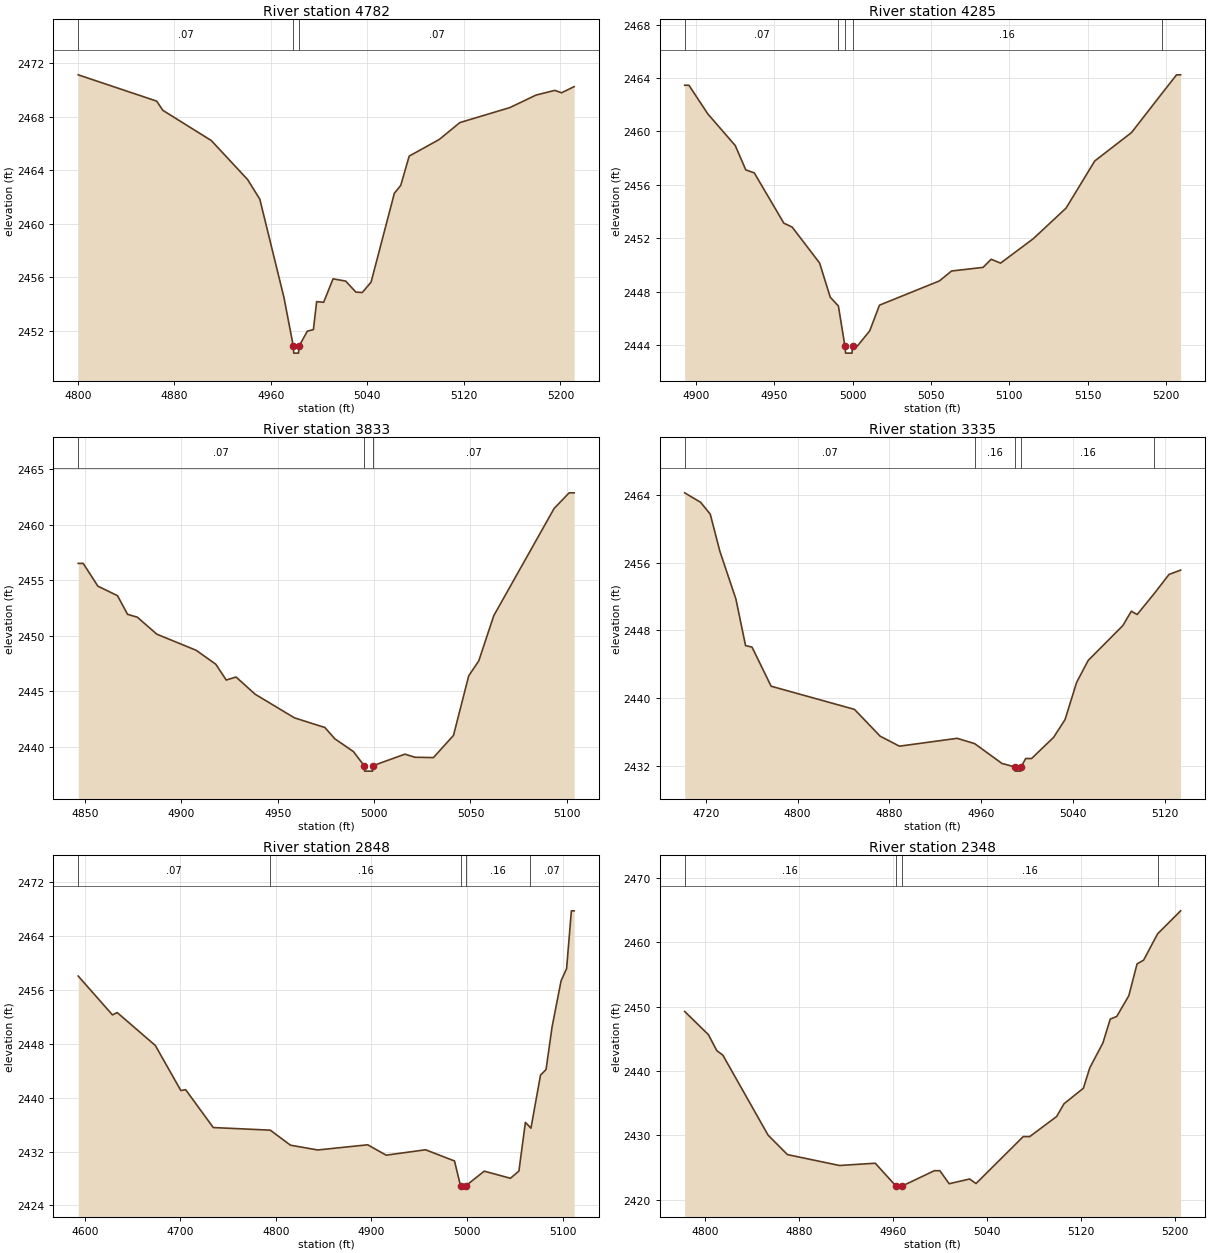
Type RM Length L Ch R = 1,4782,497,497,497
BEGIN DESCRIPTION:
Holder Creek Trib2 9.0
END DESCRIPTION:
XS GIS Cut Line= 3
      1401555.00      6809038.01      1401570.42      6808839.01
      1401505.00      6808637.99
#Sta/Elev= 30
  4800.4 2471.11  4865.4 2469.15  4870.6 2468.46  4910.7 2466.21  4940.8 2463.30
  4950.9 2461.84  4970.9 2454.51  4978.7 2450.86  4979.0 2450.36  4983.0 2450.36
  4983.3 2450.86  4990.3 2452.00  4995.3 2452.11  4998.0 2454.20  5003.8 2454.15
  5011.6 2455.90  5022.1 2455.73  5030.5 2454.91  5035.8 2454.88  5043.1 2455.65
  5062.4 2462.28  5067.7 2462.87  5074.7 2465.05  5099.6 2466.29  5116.7 2467.55
  5158.2 2468.67  5179.8 2469.60  5195.4 2469.95  5200.9 2469.77  5211.4 2470.23
#Mann=3,-1,0
  4800.4    0.07       0  4978.7    0.07       0  4983.3    0.07       0
Bank Sta=4978.7,4983.3
Exp/Cntr=0.3,0.1

Type RM Length L Ch R = 1,4285,452,452,452
BEGIN DESCRIPTION:
Holder Creek Trib2 8.0
END DESCRIPTION:
XS GIS Cut Line= 3
      1402054.99      6808787.99      1402015.19      6808688.45
      1401955.00      6808487.99
#Sta/Elev= 30
  4892.8 2463.46  4895.5 2463.46  4907.6 2461.31  4925.1 2458.94  4931.8 2457.12
  4937.2 2456.90  4956.1 2453.13  4961.4 2452.84  4978.9 2450.15  4985.7 2447.59
  4990.9 2446.93  4995.1 2443.90  4995.5 2443.40  4999.6 2443.40  4999.9 2443.90
  5002.8 2443.90  5010.9 2445.07  5017.1 2446.99  5055.4 2448.81  5063.1 2449.55
  5083.2 2449.82  5088.4 2450.43  5094.4 2450.14  5115.3 2451.97  5136.2 2454.26
  5154.5 2457.79  5178.0 2459.92  5197.4 2462.85  5206.7 2464.24  5209.3 2464.24
#Mann=5,-1,0
  4892.8    0.07       0  4990.9    0.16       0  4995.1    0.07       0
  4999.9    0.16       0  5197.4    0.07       0
Bank Sta=4995.1,4999.9
Exp/Cntr=0.3,0.1

Type RM Length L Ch R = 1,3833,498,498,498
BEGIN DESCRIPTION:
Holder Creek Trib2 7.0
END DESCRIPTION:
XS GIS Cut Line= 3
      1402404.99      6808738.03      1402434.87      6808587.46
      1402405.01      6808488.05
#Sta/Elev= 30
  4846.5 2456.51  4849.1 2456.51  4856.7 2454.46  4866.9 2453.60  4872.1 2451.92
  4877.2 2451.66  4887.3 2450.13  4907.7 2448.68  4917.9 2447.42  4923.3 2446.00
  4928.4 2446.27  4938.3 2444.72  4958.7 2442.59  4974.5 2441.72  4979.6 2440.71
  4989.3 2439.55  4994.8 2438.29  4995.1 2437.79  4999.2 2437.79  4999.6 2438.29
  5016.0 2439.32  5021.2 2439.04  5030.8 2439.01  5041.2 2441.01  5049.1 2446.38
  5054.3 2447.72  5062.1 2451.80  5093.4 2461.46  5101.2 2462.87  5103.8 2462.87
#Mann=3,-1,0
  4846.5    0.07       0  4994.8    0.07       0  4999.6    0.07       0
Bank Sta=4994.8,4999.6
Exp/Cntr=0.3,0.1

Type RM Length L Ch R = 1,3335,487,487,487
BEGIN DESCRIPTION:
Holder Creek Trib2 6.0
END DESCRIPTION:
XS GIS Cut Line= 3
      1402954.99      6808687.98      1402821.52      6808420.98
      1402805.00      6808288.00
#Sta/Elev= 30
  4701.5 2464.26  4715.4 2463.14  4723.8 2461.74  4732.2 2457.35  4746.2 2451.69
  4754.6 2446.19  4760.2 2446.02  4776.9 2441.39  4849.6 2438.65  4872.0 2435.48
  4888.8 2434.30  4939.1 2435.23  4954.4 2434.60  4978.2 2432.26  4989.3 2431.85
  4989.8 2431.35  4994.5 2431.35  4994.9 2431.85  4998.9 2432.84  5004.0 2432.84
  5023.2 2435.34  5033.2 2437.44  5043.3 2441.84  5053.4 2444.44  5083.6 2448.56
  5091.0 2450.26  5096.1 2449.87  5110.7 2452.30  5123.9 2454.61  5134.0 2455.12
#Mann=5,-1,0
  4701.5    0.07       0  4954.4    0.16       0  4989.3    0.07       0
  4994.9    0.16       0  5110.7    0.07       0
Bank Sta=4989.3,4994.9
Exp/Cntr=0.3,0.1

Type RM Length L Ch R = 1,2848,500,500,500
BEGIN DESCRIPTION:
Holder Creek Trib2 5.0
END DESCRIPTION:
XS GIS Cut Line= 3
      1403254.99      6808587.96      1403198.91      6808185.05
      1403255.00      6808087.99
#Sta/Elev= 30
  4593.2 2458.04  4629.0 2452.28  4634.0 2452.62  4673.9 2447.74  4700.6 2441.05
  4705.6 2441.18  4734.5 2435.56  4794.2 2435.17  4815.3 2432.94  4843.8 2432.23
  4896.1 2433.00  4915.4 2431.46  4956.6 2432.26  4986.9 2430.60  4993.2 2426.92
  4993.7 2426.42  4998.8 2426.92  5018.0 2429.09  5045.4 2428.03  5054.3 2429.10
  5061.1 2436.33  5065.4 2435.69  5066.9 2435.47  5076.9 2443.34  5082.7 2444.17
  5089.0 2450.49  5098.4 2457.32  5104.2 2459.15  5109.2 2467.72  5112.1 2467.72
#Mann=5,-1,0
  4593.2    0.07       0  4794.2    0.16       0  4993.2    0.07       0
  4998.8    0.16       0  5065.4    0.07       0
Bank Sta=4993.2,4998.8
Exp/Cntr=0.3,0.1

Type RM Length L Ch R = 1,2348,497,497,497
BEGIN DESCRIPTION:
Holder Creek Trib2 4.0
END DESCRIPTION:
XS GIS Cut Line= 3
      1403654.99      6808537.95      1403618.32      6808323.77
      1403705.00      6808137.99
#Sta/Elev= 30
  4782.7 2449.24  4802.9 2445.64  4810.1 2443.15  4815.2 2442.46  4853.7 2430.05
  4870.2 2427.02  4914.5 2425.33  4945.0 2425.68  4962.5 2422.16  4962.9 2421.66
  4968.1 2422.16  4995.3 2424.52  5000.0 2424.52  5007.9 2422.50  5025.3 2423.23
  5030.8 2422.53  5071.0 2429.82  5076.5 2429.81  5099.4 2432.93  5105.7 2434.91
  5122.2 2437.32  5127.7 2440.51  5138.8 2444.34  5145.1 2448.06  5150.6 2448.46
  5160.9 2451.69  5167.9 2456.62  5173.5 2457.21  5185.4 2461.29  5205.0 2464.86
#Mann=4,-1,0
  4782.7    0.16       0  4962.5    0.07       0  4968.1    0.16       0
  5185.4    0.07       0
Bank Sta=4962.5,4968.1
Exp/Cntr=0.3,0.1

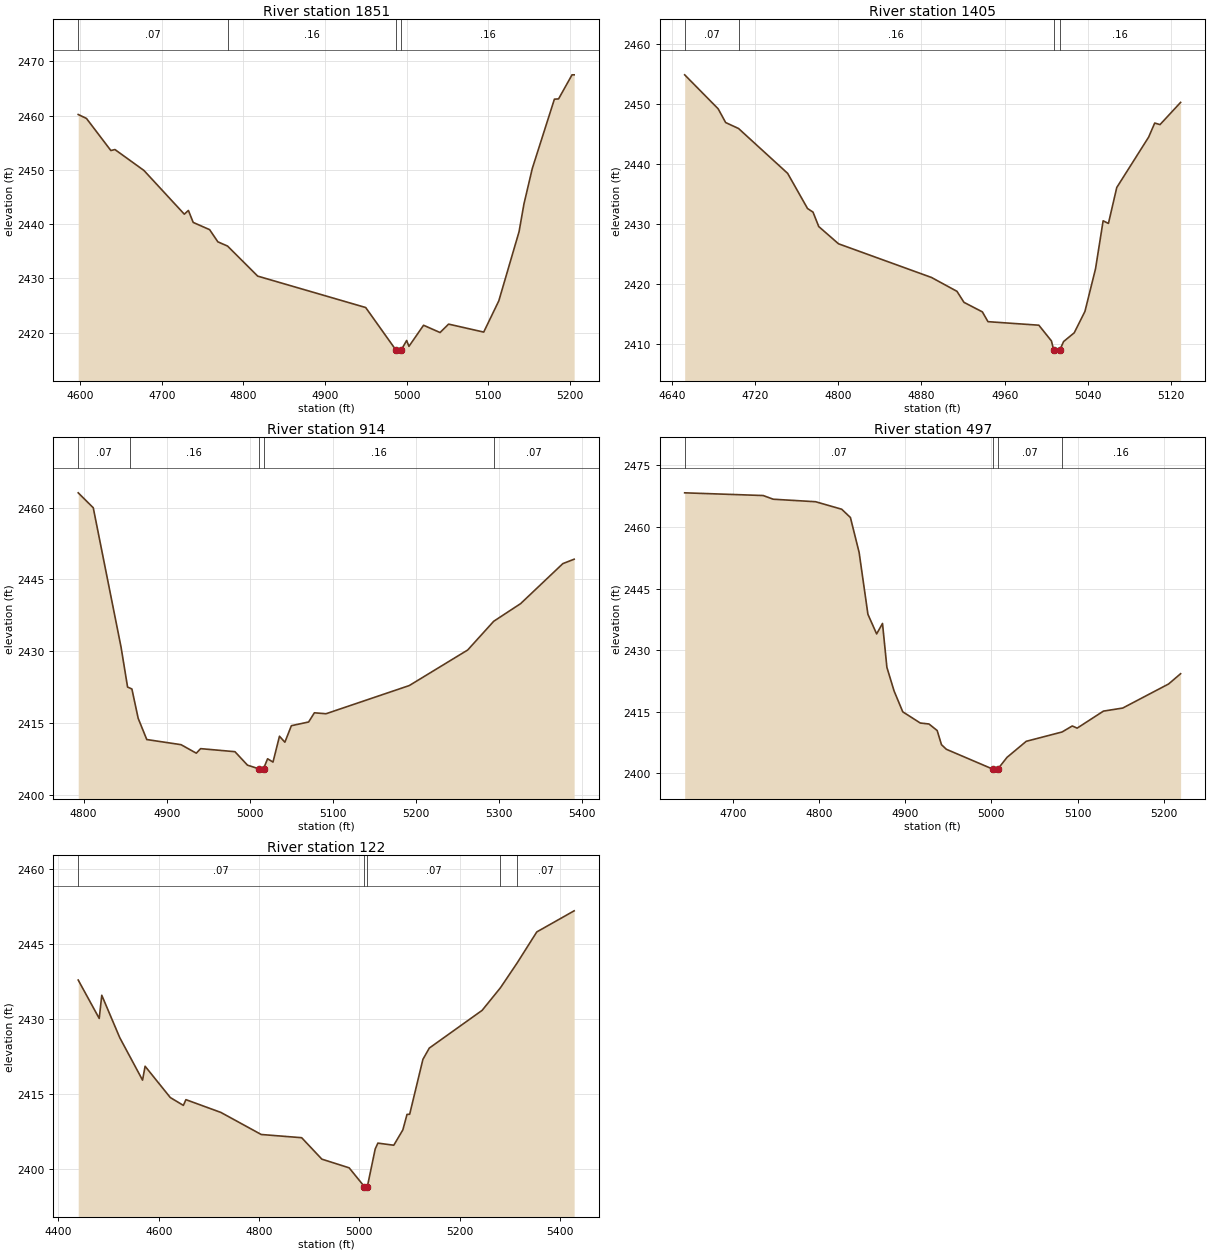
Type RM Length L Ch R = 1,1851,446,446,446
BEGIN DESCRIPTION:
Holder Creek Trib2 3.0
END DESCRIPTION:
XS GIS Cut Line= 3
      1404105.00      6808838.03      1404059.97      6808438.06
      1404105.01      6808237.97
#Sta/Elev= 30
  4597.5 2460.20  4607.6 2459.48  4637.5 2453.56  4642.5 2453.74  4678.0 2449.89
  4727.5 2441.82  4732.5 2442.51  4738.4 2440.30  4758.5 2438.97  4768.6 2436.72
  4780.5 2435.94  4817.4 2430.40  4949.7 2424.61  4987.1 2416.70  4987.5 2416.20
  4992.9 2416.70  4999.9 2418.53  5002.7 2417.45  5020.6 2421.34  5040.8 2420.00
  5051.3 2421.55  5094.3 2420.08  5112.8 2425.84  5137.6 2438.59  5143.6 2443.71
  5153.8 2450.24  5180.9 2463.03  5186.0 2463.08  5202.5 2467.52  5205.1 2467.52
#Mann=4,-1,0
  4597.5    0.07       0  4780.5    0.16       0  4987.1    0.07       0
  4992.9    0.16       0
Bank Sta=4987.1,4992.9
Exp/Cntr=0.3,0.1

Type RM Length L Ch R = 1,1405,491,491,491
BEGIN DESCRIPTION:
Holder Creek Trib2 2.0
END DESCRIPTION:
XS GIS Cut Line= 3
      1404355.00      6808838.00      1404481.80      6808514.35
      1404454.99      6808387.96
#Sta/Elev= 30
  4652.4 2454.89  4684.6 2449.23  4691.8 2446.94  4704.2 2445.95  4751.4 2438.48
  4770.5 2432.63  4775.8 2432.02  4781.3 2429.62  4800.3 2426.75  4889.7 2421.14
  4914.2 2418.83  4920.9 2417.00  4938.6 2415.41  4944.0 2413.78  4992.9 2413.19
  5005.0 2410.57  5007.2 2409.04  5007.7 2408.54  5013.0 2409.04  5016.7 2410.47
  5026.9 2411.92  5037.2 2415.48  5047.4 2422.59  5054.7 2430.58  5059.8 2430.14
  5067.8 2436.12  5098.5 2444.53  5104.3 2446.86  5109.4 2446.60  5129.2 2450.30
#Mann=4,-1,0
  4652.4    0.07       0  4704.2    0.16       0  5007.2    0.07       0
  5013.0    0.16       0
Bank Sta=5007.2,5013
Exp/Cntr=0.3,0.1

Type RM Length L Ch R = 1,914,417,417,417
BEGIN DESCRIPTION:
Holder Creek Trib2 1.0
END DESCRIPTION:
XS GIS Cut Line= 3
      1404955.01      6808838.03      1404905.18      6808637.63
      1404655.03      6808338.03
#Sta/Elev= 30
  4793.5 2463.10  4811.6 2459.98  4845.1 2430.82  4852.9 2422.52  4855.6 2422.31
  4858.1 2422.11  4865.7 2415.97  4876.0 2411.55  4917.2 2410.48  4935.6 2408.70
  4940.8 2409.65  4982.1 2409.01  4997.2 2406.20  5010.6 2405.45  5011.1 2404.95
  5016.5 2405.45  5021.4 2407.53  5027.9 2406.84  5035.7 2412.24  5042.2 2410.99
  5050.0 2414.44  5070.8 2415.22  5077.7 2417.14  5091.7 2416.94  5191.9 2422.83
  5262.2 2430.26  5293.5 2436.26  5325.9 2439.95  5376.7 2448.31  5390.3 2449.23
#Mann=5,-1,0
  4793.5    0.07       0  4855.6    0.16       0  5010.6    0.07       0
  5016.5    0.16       0  5293.5    0.07       0
Bank Sta=5010.6,5016.5
Exp/Cntr=0.3,0.1

Type RM Length L Ch R = 1,497,375,375,375
BEGIN DESCRIPTION:
Holder Creek Trib2 0.1
END DESCRIPTION:
XS GIS Cut Line= 3
      1405205.00      6808788.00      1405151.15      6808436.40
      1404955.04      6808338.02
#Sta/Elev= 30
  4644.3 2468.33  4735.4 2467.67  4747.0 2466.77  4796.1 2466.16  4826.4 2464.33
  4836.5 2462.31  4846.6 2453.79  4856.8 2438.71  4866.9 2433.93  4873.7 2436.48
  4878.8 2425.78  4887.1 2420.04  4897.2 2414.94  4917.5 2412.21  4927.6 2411.97
  4937.1 2410.38  4942.1 2406.93  4947.8 2405.80  5001.5 2400.98  5002.0 2400.48
  5007.4 2400.98  5018.1 2403.84  5040.4 2407.75  5081.9 2410.02  5093.8 2411.49
  5099.4 2410.96  5129.9 2415.11  5152.3 2415.86  5205.5 2421.73  5219.4 2424.23
#Mann=4,-1,0
  4644.3    0.07       0  5001.5    0.07       0  5007.4    0.07       0
  5081.9    0.16       0
Bank Sta=5001.5,5007.4
Exp/Cntr=0.3,0.1

Type RM Length L Ch R = 1,122,0,0,0
BEGIN DESCRIPTION:
Holder Creek Trib2 4343
END DESCRIPTION:
XS GIS Cut Line= 3
      1405325.63      6808650.32      1405257.41      6808093.89
      1404850.79      6807959.05
#Sta/Elev= 30
  4439.4 2437.77  4481.3 2430.11  4486.4 2434.73  4522.3 2426.26  4567.7 2417.80
  4572.8 2420.57  4623.1 2414.32  4649.1 2412.76  4654.2 2413.90  4723.8 2411.36
  4804.4 2406.95  4885.0 2406.31  4925.3 2402.03  4979.7 2400.30  5010.1 2396.55
  5010.6 2396.05  5016.0 2396.55  5031.7 2404.07  5037.0 2405.23  5068.7 2404.81
  5086.8 2407.87  5095.1 2410.96  5100.4 2410.99  5126.8 2421.94  5139.5 2424.19
  5244.9 2431.72  5281.5 2436.24  5315.0 2441.22  5353.9 2447.37  5428.4 2451.58
#Mann=5,-1,0
  4439.4    0.07       0  5010.1    0.07       0  5016.0    0.07       0
  5281.5    0.16       0  5315.0    0.07       0
Bank Sta=5010.1,5016
Exp/Cntr=0.3,0.1

Chan Stop Cuts=-1