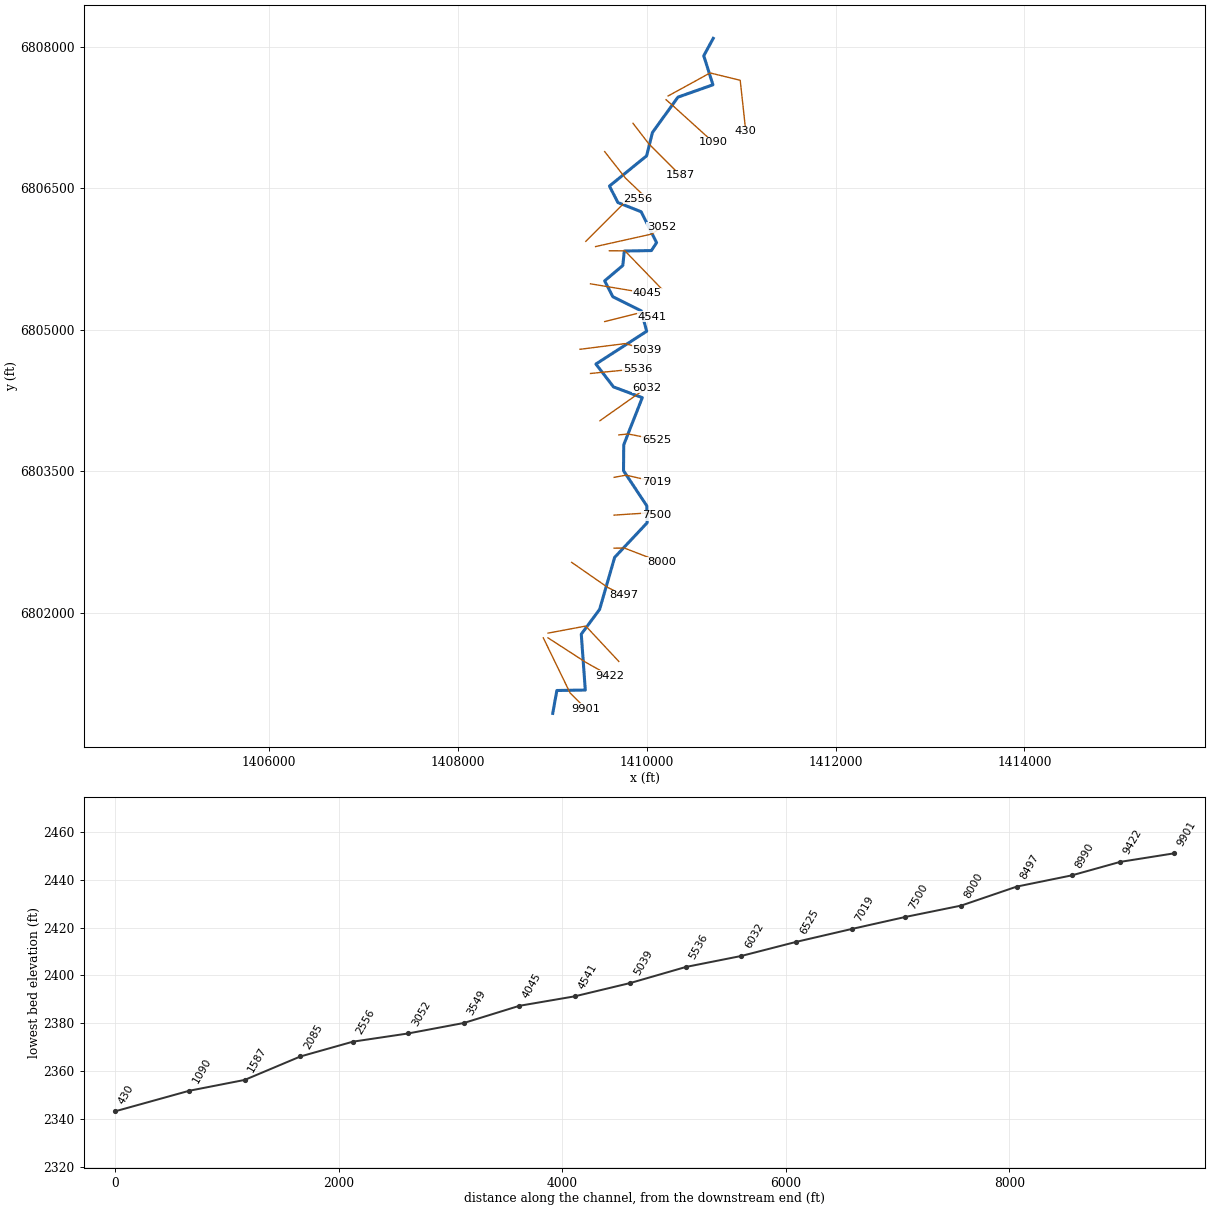
--- Holder Creek Trib3.prj (project) ---

Proj Title=Holder Creek Trib3 Base Level Engineering
Current Plan=p01
Default Exp/Contr=0.3,0.1
English Units
Geom File=g01
Flow File=f01
Plan File=p01
Y Axis Title=Elevation
X Axis Title(PF)=Main Channel Distance
X Axis Title(XS)=Station
BEGIN DESCRIPTION:
Holder Creek Trib3
END DESCRIPTION:
DSS Export Rating Curves= 0
DSS Export Rating Curve Sorted= 0
DSS Export Volume Flow Curves= 0
DXF OffsetX= 0
DXF OffsetY= 0
DXF ScaleX= 1
DXF ScaleY= 10

--- Holder Creek Trib3.p01 (plan) ---

Plan Title=Multiple Run
Short Identifier=Multiple
Geom File=g01
Flow File=f01
Subcritical Flow
K Sum by GR= 0
Std Step Tol= 0.01
Critical Tol= 0.01
Num of Std Step Trials= 20
Max Error Tol= 0.3
Flow Tol Ratio= 0.001
Split Flow NTrial= 30
Split Flow Tol= 0.02
Split Flow Ratio= 0.02
Log Output Level= 0
Friction Slope Method= 1
Unsteady Friction Slope Method= 2
Unsteady Bridges Friction Slope Method= 1
Parabolic Critical Depth
Global Vel Dist=  1 , 1 , 1
Global Log Level= 0
CheckData=True
Encroach Param= -1, 0, 0, 0
BEGIN DESCRIPTION:
Multiple Run
END DESCRIPTION:

--- Holder Creek Trib3.f01 (steady flow) ---

Flow Title=Multiple
Program Version=4.10
Number of Profiles= 7
Profile Names=10-year,25-year,50-year,1pct_min,100-year,1pct_plu,500-year
River Rch & RM=Holder Creek Tri,Reach-1         ,9901
     495     724     923     585    1166    2327    1887
River Rch & RM=Holder Creek Tri,Reach-1         ,2085
     518     759     968     613    1224    2442    1983
Boundary for River Rch & Prof#=Holder Creek Tri,Reach-1         , 1
Up Type= 0
Dn Type= 3
Dn Slope=0.009
Boundary for River Rch & Prof#=Holder Creek Tri,Reach-1         , 2
Up Type= 0
Dn Type= 3
Dn Slope=0.009
Boundary for River Rch & Prof#=Holder Creek Tri,Reach-1         , 3
Up Type= 0
Dn Type= 3
Dn Slope=0.009
Boundary for River Rch & Prof#=Holder Creek Tri,Reach-1         , 4
Up Type= 0
Dn Type= 3
Dn Slope=0.009
Boundary for River Rch & Prof#=Holder Creek Tri,Reach-1         , 5
Up Type= 0
Dn Type= 3
Dn Slope=0.009
Boundary for River Rch & Prof#=Holder Creek Tri,Reach-1         , 6
Up Type= 0
Dn Type= 3
Dn Slope=0.009
Boundary for River Rch & Prof#=Holder Creek Tri,Reach-1         , 7
Up Type= 0
Dn Type= 3
Dn Slope=0.009
DSS Import GetInterval= 0
DSS Import GetPeak= 0
DSS Import FillOption= 0

--- Holder Creek Trib3.g01 (geometry) ---

Geom Title=Existing Conditions
Program Version=4.10

River Reach=Holder Creek Tri,Reach-1
Reach XY= 30
        1409005.        6800938.       1409048.5      6801180.38
      1409349.66      6801185.26      1409307.18      6801776.71
      1409501.39       6802039.5      1409660.76      6802590.53
      1410004.75      6802956.58      1410001.25      6803136.45
       1409754.6      6803508.13      1409756.94      6803782.29
      1409953.46      6804282.15      1409648.81      6804395.82
      1409462.28       6804638.1      1410000.03      6804985.42
      1409941.74      6805201.65      1409641.34      6805351.26
      1409554.84      6805519.26      1409747.18      6805681.81
      1409762.62      6805834.93      1410049.79      6805840.09
      1410104.84      6805923.82      1409941.38      6806251.24
      1409695.17      6806348.47      1409605.74      6806523.26
      1409999.44      6806843.62      1410060.81      6807090.29
      1410331.16      6807465.15      1410701.87      6807596.02
      1410604.47      6807903.19        1410705.        6808088.

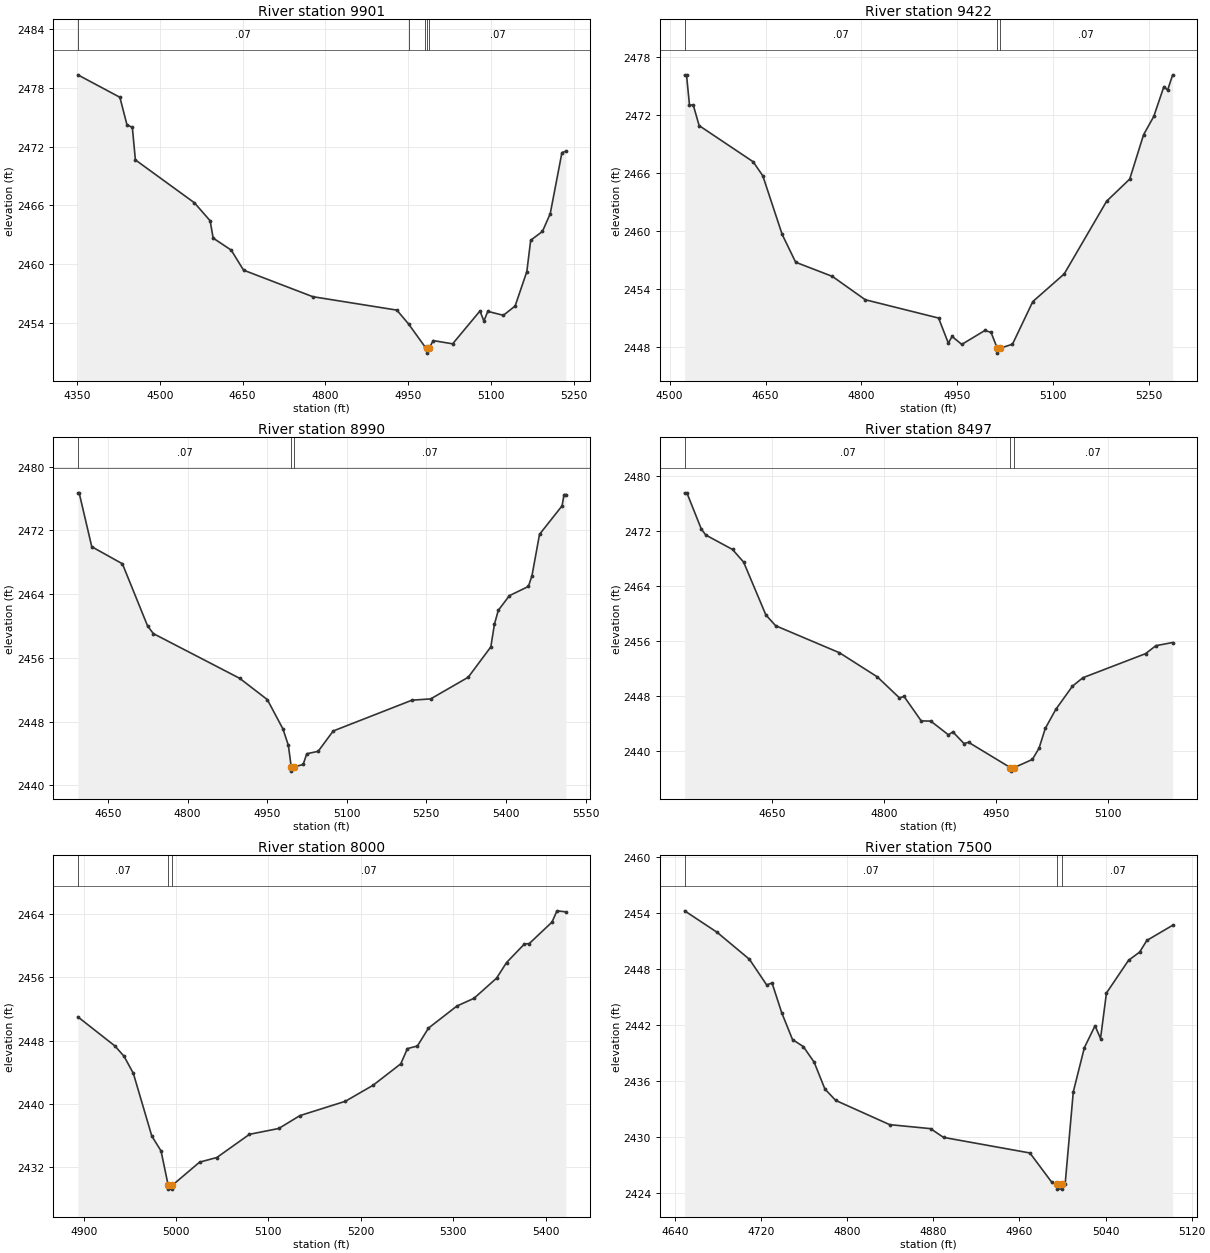
Type RM Length L Ch R = 1 ,9901    ,479,479,479
BEGIN DESCRIPTION:
Holder Creek Trib3 18.0
END DESCRIPTION:
XS GIS Cut Line= 3
      1408904.98      6801738.04      1409188.44      6801154.87
      1409355.02      6800987.98
#Sta/Elev= 30
  4351.6 2479.33  4427.8 2477.04  4440.6 2474.24  4450.4 2473.96  4455.9 2470.65
  4562.9 2466.27  4591.3 2464.44  4596.8 2462.67  4629.6 2461.44  4651.8  2459.4
  4777.3 2456.69  4929.6 2455.32  4950.8 2453.91  4981.3 2451.52  4983.8 2451.43
    4984 2450.93  4987.9 2451.43  4995.5 2452.21  5030.7 2451.88  5080.2 2455.23
  5087.3 2454.21  5094.4 2455.19  5122.6 2454.79  5143.9 2455.74  5165.1 2459.25
  5172.1 2462.45  5193.4 2463.35  5207.5 2465.16  5228.7 2471.39  5235.8 2471.53
#Mann= 5 ,-1 , 0
  4351.6     .07       0  4950.8     .16       0  4981.3     .07       0
  4983.8     .07       0  4987.9     .07       0
Bank Sta=4983.8,4987.9
XS Rating Curve= 0 ,0
Exp/Cntr=0.3,0.1

Type RM Length L Ch R = 1 ,9422    ,432,432,432
BEGIN DESCRIPTION:
Holder Creek Trib3 17.0
END DESCRIPTION:
XS GIS Cut Line= 3
      1408955.01      6801737.99      1409355.05      6801478.93
      1409604.96      6801338.02
#Sta/Elev= 30
  4523.4 2476.07  4526.4 2476.07    4531    2473  4536.9 2472.99  4546.1 2470.87
  4630.6 2467.14  4645.7 2465.69    4676 2459.64  4697.1 2456.77  4754.5 2455.31
    4806  2452.9  4920.7 2451.01  4935.9 2448.43  4941.8 2449.11    4957 2448.29
  4993.2 2449.73  5002.8 2449.53  5012.5 2447.89  5012.8 2447.39  5016.7 2447.89
  5036.3 2448.31  5068.1 2452.71  5117.2 2455.56  5183.6 2463.07  5219.7 2465.35
  5241.4 2469.93  5257.3 2471.81  5273.2  2474.9    5279 2474.53  5286.9 2476.11
#Mann= 3 ,-1 , 0
  4523.4     .07       0  5012.5     .07       0  5016.7     .07       0
Bank Sta=5012.5,5016.7
XS Rating Curve= 0 ,0
Exp/Cntr=0.3,0.1

Type RM Length L Ch R = 1 ,8990    ,493,493,493
BEGIN DESCRIPTION:
Holder Creek Trib3 16.0
END DESCRIPTION:
XS GIS Cut Line= 3
      1408955.01        6801788.      1409354.97      6801862.86
      1409705.01      6801487.98
#Sta/Elev= 30
  4593.1 2476.72  4595.6 2476.72  4619.4 2469.95  4677.1 2467.81  4724.6    2460
  4735.5 2459.04  4898.3 2453.42  4950.3 2450.75  4979.7 2447.07  4989.9 2445.01
  4995.4 2442.27  4995.6 2441.77  4999.6 2442.27  5017.8 2442.61  5024.6 2443.95
  5046.1 2444.26  5074.4 2446.81  5222.9 2450.68  5258.1 2450.84  5328.9 2453.56
  5371.5 2457.37  5378.3 2460.22  5385.6 2461.97  5406.6 2463.81  5442.3 2464.96
  5449.1 2466.33  5463.3 2471.51  5505.8 2475.09  5509.5  2476.5  5512.9  2476.5
#Mann= 3 ,-1 , 0
  4593.1     .07       0  4995.4     .07       0  4999.6     .07       0
Bank Sta=4995.4,4999.6
XS Rating Curve= 0 ,0
Exp/Cntr=0.3,0.1

Type RM Length L Ch R = 1 ,8497    ,497,497,497
BEGIN DESCRIPTION:
Holder Creek Trib3 15.0
END DESCRIPTION:
XS GIS Cut Line= 3
      1409205.01      6802537.99      1409588.19      6802271.39
      1409755.01        6802188.
#Sta/Elev= 30
  4533.2 2477.52  4536.2 2477.52  4555.5 2472.27  4561.5 2471.39  4597.3 2469.29
  4612.2 2467.45  4641.9 2459.79    4655 2458.21  4740.5 2454.28  4791.1 2450.78
  4820.8 2447.72  4826.9 2447.94  4849.9 2444.38  4862.7 2444.35  4886.3 2442.36
  4892.3 2442.78  4907.2 2441.09  4913.3 2441.27  4969.4 2437.58  4969.7 2437.08
    4974 2437.58  4998.6 2438.77  5007.6  2440.4    5016 2443.29    5030 2446.04
  5052.3 2449.42  5066.3 2450.65  5150.2 2454.15  5164.1 2455.31  5186.5 2455.77
#Mann= 3 ,-1 , 0
  4533.2     .07       0  4969.4     .07       0    4974     .07       0
Bank Sta=4969.4,4974
XS Rating Curve= 0 ,0
Exp/Cntr=0.3,0.1

Type RM Length L Ch R = 1 ,8000    ,500,500,500
BEGIN DESCRIPTION:
Holder Creek Trib3 14.0
END DESCRIPTION:
XS GIS Cut Line= 3
      1409654.95        6802688.      1409761.24      6802689.86
      1410154.97      6802538.01
#Sta/Elev= 30
  4893.7 2451.01  4933.8 2447.32  4943.8    2446  4953.8 2443.84  4973.8 2435.89
  4983.8    2434  4991.5 2429.66  4991.8 2429.16  4995.8 2429.16  4996.1 2429.66
  5025.5 2432.58  5044.2 2433.17  5079.5 2436.11  5111.2 2436.85  5134.1 2438.48
  5183.3  2440.3  5213.3 2442.33  5243.3 2445.05  5250.5 2446.98  5261.3 2447.31
  5273.3 2449.58  5304.1 2452.38  5322.5 2453.35    5347 2455.91  5357.8 2457.89
  5377.1 2460.24  5382.4  2460.3    5407 2463.02  5412.4 2464.45    5422 2464.32
#Mann= 3 ,-1 , 0
  4893.7     .07       0  4991.5     .07       0  4996.1     .07       0
Bank Sta=4991.5,4996.1
XS Rating Curve= 0 ,0
Exp/Cntr=0.3,0.1

Type RM Length L Ch R = 1 ,7500    ,481,481,481
BEGIN DESCRIPTION:
Holder Creek Trib3 13.0
END DESCRIPTION:
XS GIS Cut Line= 3
      1409654.97        6803038.      1410005.23      6803060.77
      1410104.96      6803038.01
#Sta/Elev= 30
    4649 2454.27  4679.1 2451.97  4709.2 2449.07  4725.2 2446.32  4730.2 2446.53
  4739.2 2443.33  4749.2 2440.46  4759.3  2439.7  4769.3 2438.03  4779.3 2435.15
  4789.3 2433.93  4839.4 2431.33  4877.4  2430.9  4889.5 2429.96  4969.7 2428.29
  4989.8 2425.18  4994.9 2424.91  4995.3 2424.41  4999.4 2424.41  4999.8 2424.91
  5002.4 2424.91    5010 2434.85  5020.3 2439.59  5030.2 2441.94  5035.3 2440.57
  5040.8 2445.45  5061.3 2448.96  5071.6 2449.84  5078.3 2451.09  5102.3 2452.72
#Mann= 3 ,-1 , 0
    4649     .07       0  4994.9     .07       0  4999.8     .07       0
Bank Sta=4994.9,4999.8
XS Rating Curve= 0 ,0
Exp/Cntr=0.3,0.1

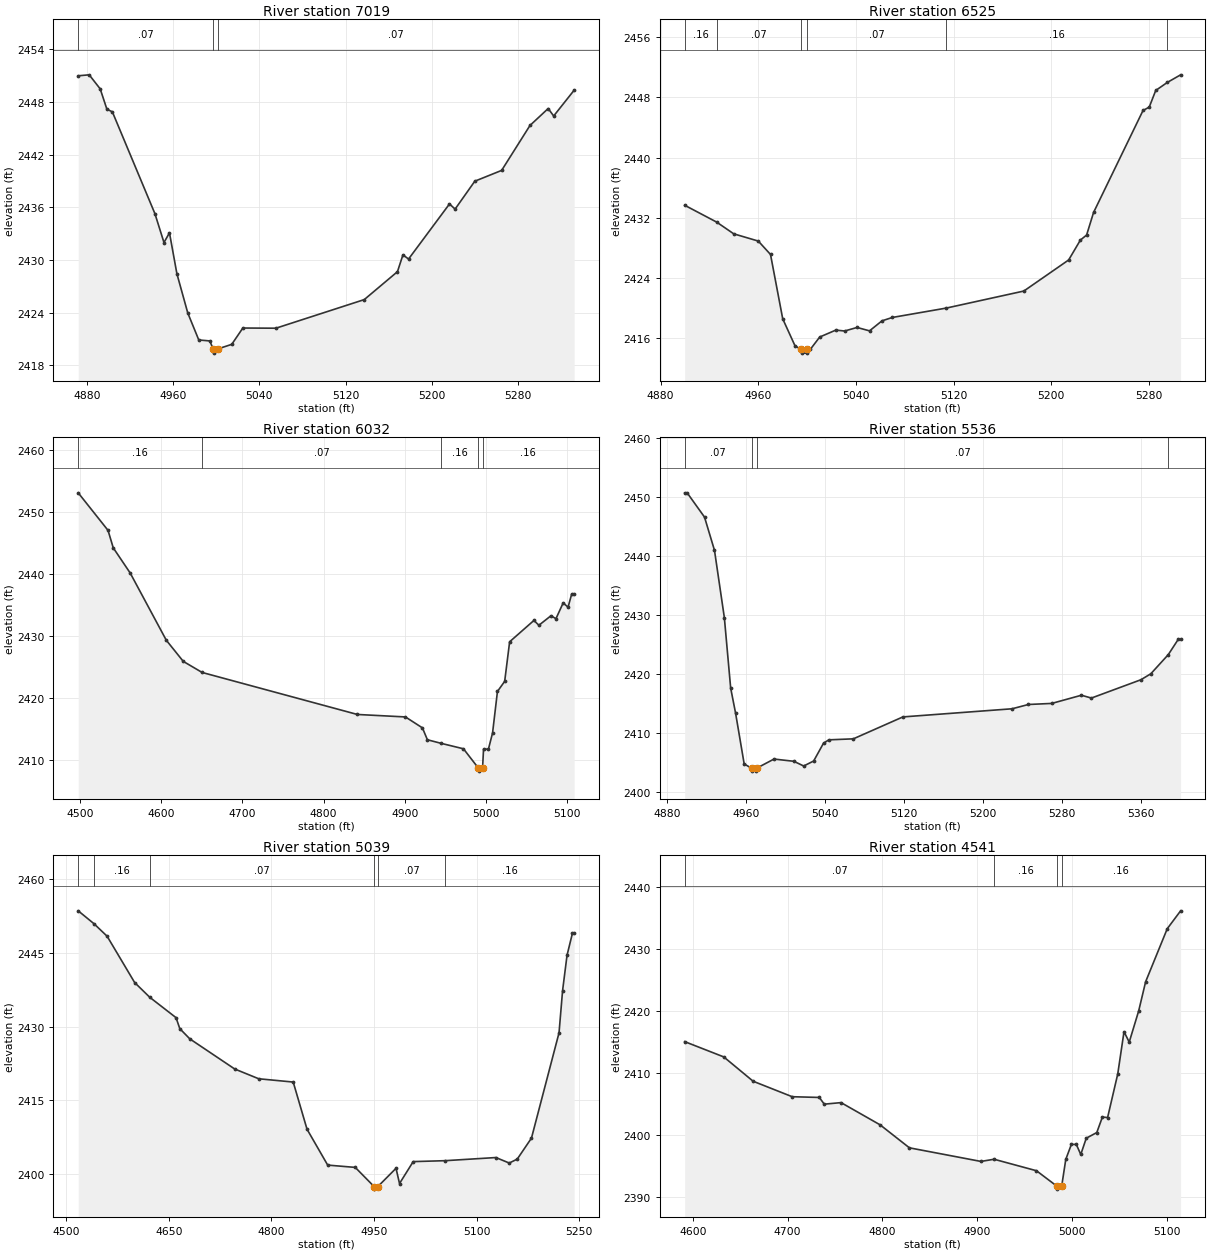
Type RM Length L Ch R = 1 ,7019    ,494,494,494
BEGIN DESCRIPTION:
Holder Creek Trib3 12.0
END DESCRIPTION:
XS GIS Cut Line= 3
      1409654.96      6803437.99      1409781.04      6803461.18
      1410104.98        6803388.
#Sta/Elev= 30
  4871.8 2450.98    4882 2451.09  4892.2 2449.49  4898.4 2447.18  4903.5 2446.87
    4943 2435.27  4951.4 2431.98  4956.5 2433.09  4963.4 2428.42  4973.5 2423.95
  4983.7 2420.88  4993.9 2420.77    4997 2419.88  4997.4 2419.38  5001.9 2419.88
  5014.3 2420.38  5024.6 2422.24  5055.3 2422.22  5137.3 2425.48  5168.1 2428.66
  5173.2 2430.58  5178.4  2430.1  5216.4 2436.38  5221.6 2435.79  5239.9 2438.97
  5264.8  2440.2  5291.1 2445.32    5308 2447.25  5313.1  2446.4  5332.1 2449.34
#Mann= 3 ,-1 , 0
  4871.8     .07       0    4997     .07       0  5001.9     .07       0
Bank Sta=4997,5001.9
XS Rating Curve= 0 ,0
Exp/Cntr=0.3,0.1

Type RM Length L Ch R = 1 ,6525    ,493,493,493
BEGIN DESCRIPTION:
Holder Creek Trib3 11.0
END DESCRIPTION:
XS GIS Cut Line= 3
      1409704.99        6803888.      1409804.88      6803897.14
        1410105.        6803838.
#Sta/Elev= 30
  4899.7 2433.68  4925.9 2431.44  4939.9 2429.88    4960 2428.92    4970 2427.14
    4980 2418.59  4990.1 2414.99  4995.1 2414.53  4995.4 2414.03  4999.7 2414.03
  5000.1 2414.53  5002.6 2414.53  5010.3 2416.17  5023.5 2417.09  5030.7 2416.97
  5040.9 2417.44  5051.1 2416.99  5061.3 2418.32  5069.8 2418.77  5114.1 2420.02
  5177.5 2422.28  5214.2 2426.41  5223.8 2429.05  5228.9 2429.72  5234.6 2432.72
  5275.1 2446.27  5280.2 2446.72  5285.5 2448.93    5295    2450  5305.9 2451.01
#Mann= 6 ,-1 , 0
  4899.7     .16       0  4925.9     .07       0  4995.1     .07       0
  5000.1     .07       0  5114.1     .16       0    5295     .07       0
Bank Sta=4995.1,5000.1
XS Rating Curve= 0 ,0
Exp/Cntr=0.3,0.1

Type RM Length L Ch R = 1 ,6032    ,496,496,496
BEGIN DESCRIPTION:
Holder Creek Trib3 10.0
END DESCRIPTION:
XS GIS Cut Line= 3
      1409505.02      6804038.02      1409915.12      6804327.37
      1410004.98      6804387.99
#Sta/Elev= 30
  4498.1 2453.12  4534.8 2447.05  4541.2 2444.23  4562.1 2440.15  4606.5 2429.29
  4627.4 2425.87  4650.6 2424.08  4841.6 2417.29  4900.8 2416.89  4921.7 2415.12
  4927.8  2413.2  4944.8 2412.62  4972.2 2411.74  4990.5 2408.63  4990.9 2408.13
  4995.7 2408.63  4996.9 2411.68  5002.9 2411.68    5008  2414.3    5014 2421.01
  5022.9 2422.64    5029 2429.04  5058.9 2432.49    5065 2431.71  5079.9 2433.25
    5086 2432.77  5094.9 2435.33  5100.9 2434.63  5105.4 2436.77  5108.4 2436.77
#Mann= 5 ,-1 , 0
  4498.1     .16       0  4650.6     .07       0  4944.8     .16       0
  4990.5     .07       0  4995.7     .16       0
Bank Sta=4990.5,4995.7
XS Rating Curve= 0 ,0
Exp/Cntr=0.3,0.1

Type RM Length L Ch R = 1 ,5536    ,497,497,497
BEGIN DESCRIPTION:
Holder Creek Trib3 9.0
END DESCRIPTION:
XS GIS Cut Line= 3
      1409405.01        6804538.      1409506.45      6804548.64
      1409905.01        6804588.
#Sta/Elev= 30
    4898 2450.77  4900.5 2450.77  4918.1 2446.65  4928.2 2441.01  4938.2 2429.59
  4944.6 2417.63  4949.6 2413.36  4958.3 2404.75  4965.8 2404.04  4966.2 2403.54
  4970.6 2403.54    4971 2404.04  4988.5 2405.59  5008.6 2405.21  5018.6 2404.41
  5028.7 2405.26  5038.7 2408.29  5044.1 2408.85  5068.9 2409.02  5119.1 2412.74
  5229.7 2414.12  5246.3 2414.85  5269.9 2415.03    5300 2416.42  5310.1 2415.94
  5360.3 2419.05  5370.3 2420.06    5388 2423.31    5398 2425.88  5400.5 2425.88
#Mann= 4 ,-1 , 0
    4898     .07       0  4965.8     .07       0    4971     .07       0
    5388     .16       0
Bank Sta=4965.8,4971
XS Rating Curve= 0 ,0
Exp/Cntr=0.3,0.1

Type RM Length L Ch R = 1 ,5039    ,498,498,498
BEGIN DESCRIPTION:
Holder Creek Trib3 8.0
END DESCRIPTION:
XS GIS Cut Line= 3
      1409293.14      6804794.38      1409771.66      6804854.69
      1410005.02        6804788.
#Sta/Elev= 30
  4517.7 2453.59  4540.6 2450.98  4559.9 2448.42  4600.2 2438.97  4622.4 2435.95
  4660.7 2431.81  4666.2 2429.57  4680.8 2427.49  4746.5 2421.34  4781.6 2419.35
    4832 2418.68  4852.2 2409.06  4882.4 2401.75  4922.7 2401.28  4950.4 2397.35
  4950.8 2396.85  4955.6 2397.35  4982.3  2401.1  4987.4 2397.99  5007.4 2402.46
  5054.3 2402.65  5128.3 2403.29  5147.8 2402.17  5159.5 2402.97  5180.3 2407.25
  5220.6 2428.72  5225.8 2437.34  5232.3 2444.53  5240.1 2448.97  5242.7 2448.97
#Mann= 6 ,-1 , 0
  4517.7     .07       0  4540.6     .16       0  4622.4     .07       0
  4950.4     .07       0  4955.6     .07       0  5054.3     .16       0
Bank Sta=4950.4,4955.6
XS Rating Curve= 0 ,0
Exp/Cntr=0.3,0.1

Type RM Length L Ch R = 1 ,4541    ,496,496,496
BEGIN DESCRIPTION:
Holder Creek Trib3 7.0
END DESCRIPTION:
XS GIS Cut Line= 3
      1409554.98        6805088.      1409951.48      6805186.72
      1410054.99      6805138.01
#Sta/Elev= 30
  4591.4 2415.03  4632.6 2412.57  4663.6 2408.65  4704.8 2406.16  4733.4 2406.04
  4738.6 2404.96  4756.3 2405.21  4797.5 2401.63  4828.4 2397.93  4903.8 2395.74
  4917.7 2396.09  4962.4 2394.24  4983.7 2391.78  4984.1 2391.28    4989 2391.78
  4993.3 2396.07  4999.2 2398.48  5004.4 2398.48  5009.1 2396.86  5014.9 2399.48
    5026 2400.39  5031.9 2402.88  5037.4 2402.81  5048.1 2409.82  5054.7 2416.63
  5060.2 2414.95  5070.2 2419.99  5077.5 2424.67  5100.3 2433.21  5114.4 2436.09
#Mann= 4 ,-1 , 0
  4591.4     .07       0  4917.7     .16       0  4983.7     .07       0
    4989     .16       0
Bank Sta=4983.7,4989
XS Rating Curve= 0 ,0
Exp/Cntr=0.3,0.1

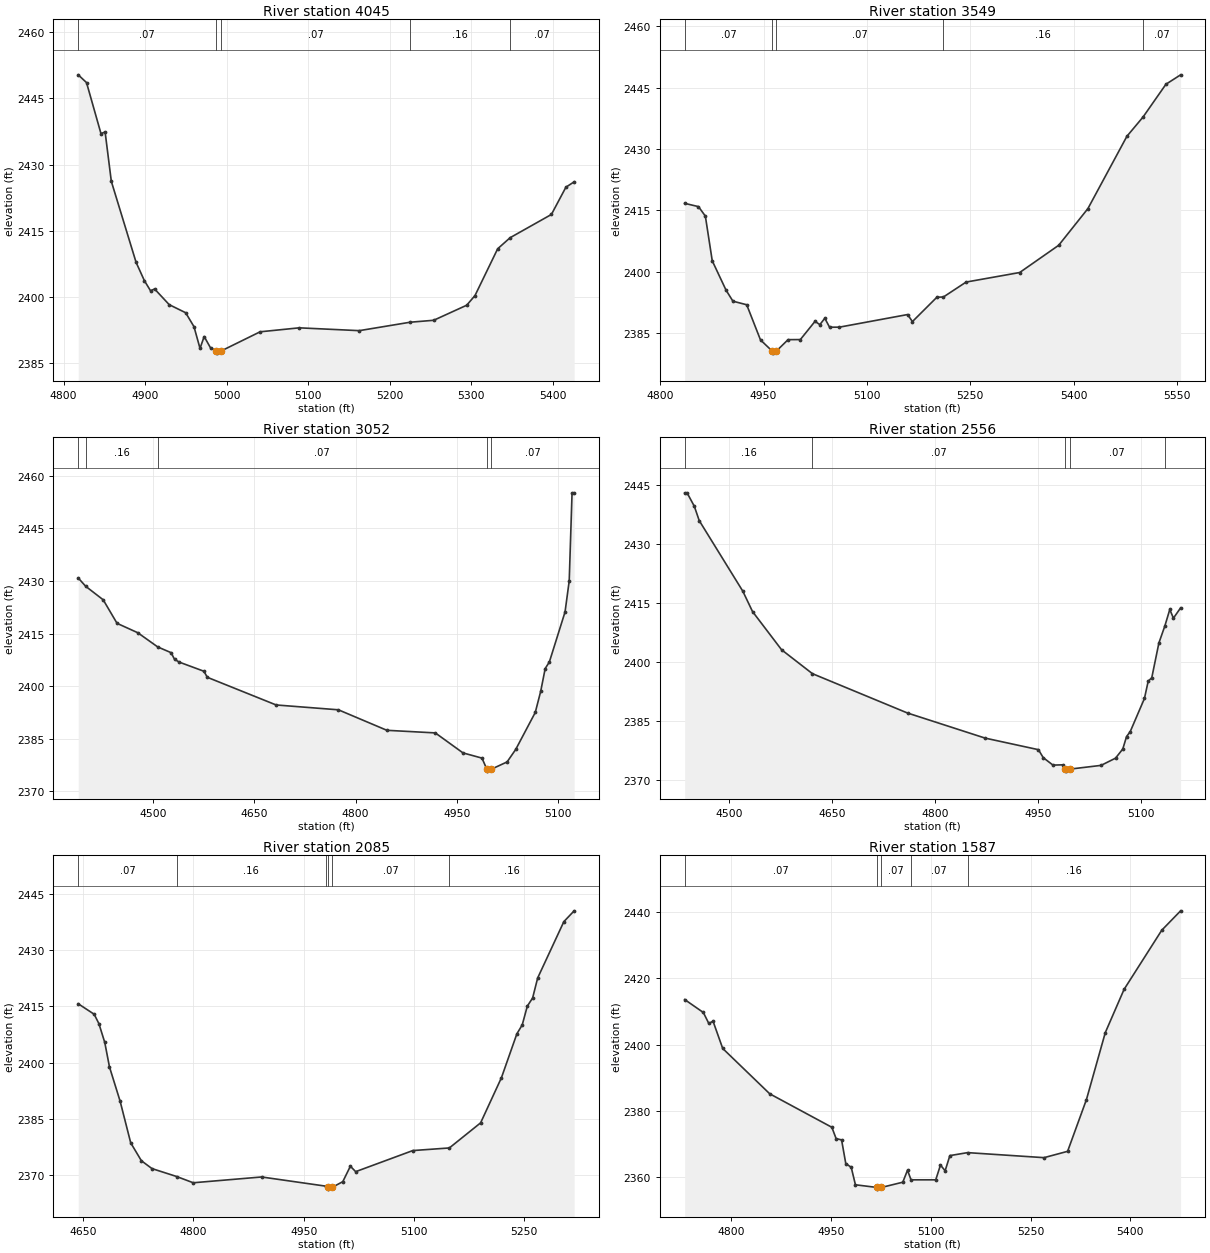
Type RM Length L Ch R = 1 ,4045    ,496,496,496
BEGIN DESCRIPTION:
Holder Creek Trib3 6.0
END DESCRIPTION:
XS GIS Cut Line= 3
      1409404.95      6805488.01      1409584.56      6805458.02
      1410004.97        6805388.
#Sta/Elev= 30
  4817.9 2450.36  4828.1  2448.6  4845.8 2437.06  4850.9  2437.4  4858.5 2426.24
  4888.9 2407.88  4899.1 2403.72  4906.6 2401.45  4911.6 2401.85  4929.5  2398.3
  4949.7 2396.47  4959.9 2393.31  4967.3 2388.39  4972.4 2391.08  4980.2 2388.51
  4987.3 2387.82  4987.8 2387.32  4993.3 2387.82    5041 2392.15    5089 2393.05
  5162.6 2392.41    5225 2394.32  5253.9 2394.76  5294.4 2398.17  5304.6 2400.37
  5332.4 2410.96  5347.7 2413.47  5398.3 2418.73  5416.1 2424.91  5426.2 2426.12
#Mann= 5 ,-1 , 0
  4817.9     .07       0  4987.3     .07       0  4993.3     .07       0
    5225     .16       0  5347.7     .07       0
Bank Sta=4987.3,4993.3
XS Rating Curve= 0 ,0
Exp/Cntr=0.3,0.1

Type RM Length L Ch R = 1 ,3549    ,497,497,497
BEGIN DESCRIPTION:
Holder Creek Trib3 5.0
END DESCRIPTION:
XS GIS Cut Line= 3
        1409605.        6805838.       1409769.4      6805837.24
      1410155.03      6805437.97
#Sta/Elev= 30
  4835.6 2416.73  4855.6 2415.93  4865.6 2413.62  4875.6  2402.7  4895.6 2395.54
  4905.6 2392.84  4925.6 2391.97  4945.6 2383.38  4962.6 2380.66  4963.1 2380.16
  4968.6 2380.66  4985.6 2383.45  5003.4 2383.47  5024.7 2387.92  5031.7 2387.12
  5038.9 2388.67  5045.8 2386.49    5060  2386.5    5159 2389.58    5166 2387.86
  5201.5 2393.81    5211 2393.87  5243.9 2397.51  5321.6 2399.84  5378.2 2406.49
  5420.6 2415.45  5477.2 2433.11  5500.6 2437.81  5533.8 2445.81  5555.1 2448.11
#Mann= 5 ,-1 , 0
  4835.6     .07       0  4962.6     .07       0  4968.6     .07       0
    5211     .16       0  5500.6     .07       0
Bank Sta=4962.6,4968.6
XS Rating Curve= 0 ,0
Exp/Cntr=0.3,0.1

Type RM Length L Ch R = 1 ,3052    ,496,496,496
BEGIN DESCRIPTION:
Holder Creek Trib3 4.0
END DESCRIPTION:
XS GIS Cut Line= 3
      1409458.88       6805882.4      1410054.95      6806015.25
        1410155.        6806088.
#Sta/Elev= 30
  4389.3 2430.83  4400.5 2428.44  4426.3 2424.61  4446.8 2417.91  4477.5 2415.23
    4507 2411.19  4526.8 2409.55  4531.9 2407.67    4539 2406.85  4575.4 2404.26
  4580.5 2402.53  4682.4 2394.65  4774.6 2393.27  4846.4 2387.43  4918.1 2386.69
  4959.1 2380.99  4987.2 2379.51  4994.5  2376.3    4995  2375.8  5000.5  2376.3
  5024.4 2378.42  5037.2 2381.99  5066.1 2392.51  5074.2 2398.56  5080.8 2405.02
    5087 2406.91  5110.2 2421.14  5116.4 2430.01  5120.6 2455.09  5123.7 2455.09
#Mann= 5 ,-1 , 0
  4389.3     .07       0  4400.5     .16       0    4507     .07       0
  4994.5     .07       0  5000.5     .07       0
Bank Sta=4994.5,5000.5
XS Rating Curve= 0 ,0
Exp/Cntr=0.3,0.1

Type RM Length L Ch R = 1 ,2556    ,471,471,471
BEGIN DESCRIPTION:
Holder Creek Trib3 3.0
END DESCRIPTION:
XS GIS Cut Line= 3
      1409355.02      6805938.02      1409754.85      6806337.64
      1409905.03      6806388.01
#Sta/Elev= 30
  4434.7 2443.06  4438.2 2443.06  4448.8 2439.63  4455.9 2436.01  4519.5 2418.08
  4533.7  2412.9  4576.1 2403.19  4621.1 2397.12  4759.9 2387.12  4873.1 2380.75
  4950.9 2377.81  4957.9 2375.79  4972.1 2373.89  4986.2 2373.96  4990.2 2372.86
  4990.7 2372.36  4996.3 2372.86  5042.3 2373.82  5063.4 2375.65    5074 2377.98
  5079.5 2381.14  5084.8 2382.37  5105.6 2390.82  5111.1 2395.21  5116.3 2396.08
  5126.7 2404.92  5135.5 2409.29  5142.6 2413.43  5147.9 2411.22  5158.4 2413.84
#Mann= 5 ,-1 , 0
  4434.7     .16       0  4621.1     .07       0  4990.2     .07       0
  4996.3     .07       0  5135.5     .16       0
Bank Sta=4990.2,4996.3
XS Rating Curve= 0 ,0
Exp/Cntr=0.3,0.1

Type RM Length L Ch R = 1 ,2085    ,498,498,498
BEGIN DESCRIPTION:
Holder Creek Trib3 2.0
END DESCRIPTION:
XS GIS Cut Line= 3
      1409554.99      6806888.02      1409775.47      6806607.62
      1410005.02      6806387.98
#Sta/Elev= 30
  4643.3 2415.73    4665 2412.93  4671.4 2410.43  4679.4 2405.39  4685.8 2398.85
  4700.3 2389.67  4714.7 2378.54  4729.2 2373.76  4743.6 2371.66  4777.2 2369.54
  4799.7 2367.87  4892.7 2369.42  4979.8 2366.97  4982.7 2366.67  4983.2 2366.17
  4988.9 2366.67  5003.1 2368.17  5013.4  2372.3  5020.6 2370.84  5098.3 2376.48
    5148 2377.18  5190.5 2383.89  5218.8 2395.95  5239.8 2407.69  5247.1 2410.08
    5254  2415.1  5261.2 2417.26  5268.1 2422.63  5303.7 2437.69  5317.7 2440.58
#Mann= 6 ,-1 , 0
  4643.3     .07       0  4777.2     .16       0  4979.8     .07       0
  4982.7     .07       0  4988.9     .07       0    5148     .16       0
Bank Sta=4982.7,4988.9
XS Rating Curve= 0 ,0
Exp/Cntr=0.3,0.1

Type RM Length L Ch R = 1 ,1587    ,497,497,497
BEGIN DESCRIPTION:
Holder Creek Trib3 1.0
END DESCRIPTION:
XS GIS Cut Line= 3
      1409855.01      6807187.98      1410019.34      6806974.63
      1410355.01      6806637.99
#Sta/Elev= 30
  4730.7 2413.63  4758.7 2409.72  4766.9 2406.42  4773.3 2407.08  4787.8 2398.86
  4858.4 2385.17  4951.7 2375.06  4958.1 2371.64  4966.3 2371.26  4972.6 2364.12
  4980.8 2362.97  4987.1  2357.7  5019.7 2356.89  5020.2 2356.39    5026 2356.89
  5058.2 2358.48  5065.3  2362.1  5070.6  2359.2  5107.7  2359.2  5114.8 2363.66
  5121.8 2361.93  5128.9 2366.51  5155.5 2367.41  5270.3 2365.89  5305.7  2367.8
    5334 2383.44  5362.3 2403.65  5390.5  2416.7  5447.1 2434.56  5475.4 2440.41
#Mann= 5 ,-1 , 0
  4730.7     .07       0  5019.7     .07       0    5026     .07       0
  5070.6     .07       0  5155.5     .16       0
Bank Sta=5019.7,5026
XS Rating Curve= 0 ,0
Exp/Cntr=0.3,0.1

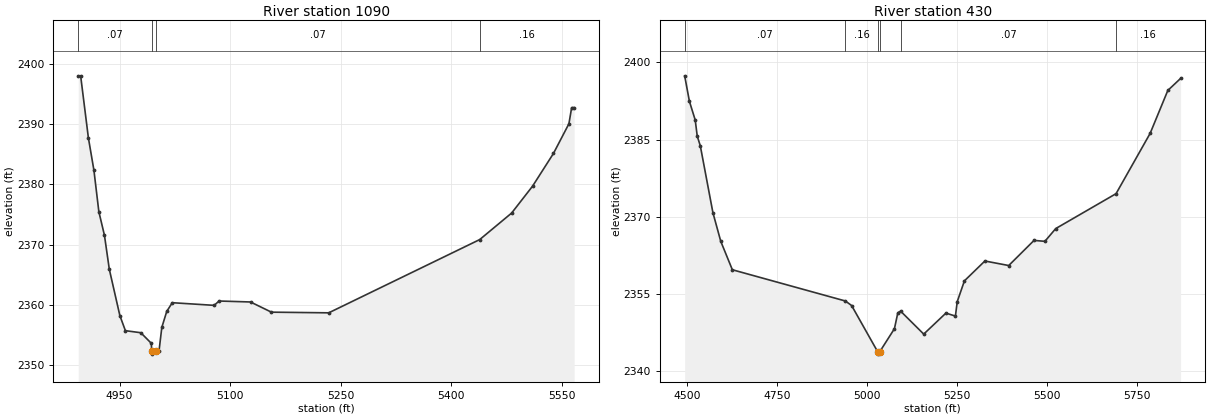
Type RM Length L Ch R = 1 ,1090    ,660,660,660
BEGIN DESCRIPTION:
Holder Creek Trib3 0.1
END DESCRIPTION:
XS GIS Cut Line= 3
      1410205.01      6807437.99      1410284.82      6807368.08
      1410705.02      6806987.99
#Sta/Elev= 30
  4893.9 2398.02  4897.2 2398.02  4907.7 2387.73  4915.2 2382.36  4921.9 2375.48
  4929.5 2371.56  4936.1 2365.92  4950.4 2358.25  4957.9 2355.75  4978.8 2355.41
  4993.1 2353.65  4993.6 2352.36  4994.1 2351.86  4999.9 2352.36  5003.5 2352.36
  5007.3 2356.29    5014 2358.95  5021.5 2360.39  5078.3 2359.95    5085 2360.67
  5127.6 2360.51    5156 2358.82  5233.7 2358.71  5438.5 2370.86  5481.8 2375.26
  5510.2 2379.72  5538.5 2385.14  5559.5 2390.07  5563.2 2392.74  5566.6 2392.74
#Mann= 4 ,-1 , 0
  4893.9     .07       0  4993.6     .07       0  4999.9     .07       0
  5438.5     .16       0
Bank Sta=4993.6,4999.9
XS Rating Curve= 0 ,0
Exp/Cntr=0.3,0.1

Type RM Length L Ch R = 1 ,430     ,0,0,0
BEGIN DESCRIPTION:
Holder Creek Trib3 4113
END DESCRIPTION:
XS GIS Cut Line= 4
      1410226.92       6807477.5      1410672.04      6807721.47
      1410990.61      6807643.59      1411049.64      6807102.65
#Sta/Elev= 30
  4492.4 2397.38  4505.6 2392.42  4521.7  2388.8  4527.4 2385.64  4535.8 2383.81
    4571 2370.78  4592.8 2365.23    4625 2359.71  4939.5 2353.64  4956.8 2352.76
    5029 2343.82  5029.5 2343.32  5035.4 2343.82 5075.95 2348.26  5085.4 2351.35
  5093.1 2351.67 5157.42 2347.21  5219.2 2351.29  5245.6 2350.71  5250.7 2353.53
  5270.7 2357.56  5327.6 2361.41  5393.9 2360.53  5464.3 2365.41  5494.5 2365.23
  5524.7 2367.71  5692.5 2374.49  5787.3  2386.2  5836.5 2394.54  5872.1 2396.88
#Mann= 6 ,-1 , 0
  4492.4     .07       0  4939.5     .16       0    5029     .05       0
  5035.4     .05       0  5093.1     .07       0  5692.5     .16       0
Bank Sta=5029,5035.4
XS Rating Curve= 0 ,0
Exp/Cntr=0.3,0.1

Chan Stop Cuts=-1
Use User Specified Reach Order=0
Composite Channel Slope=5