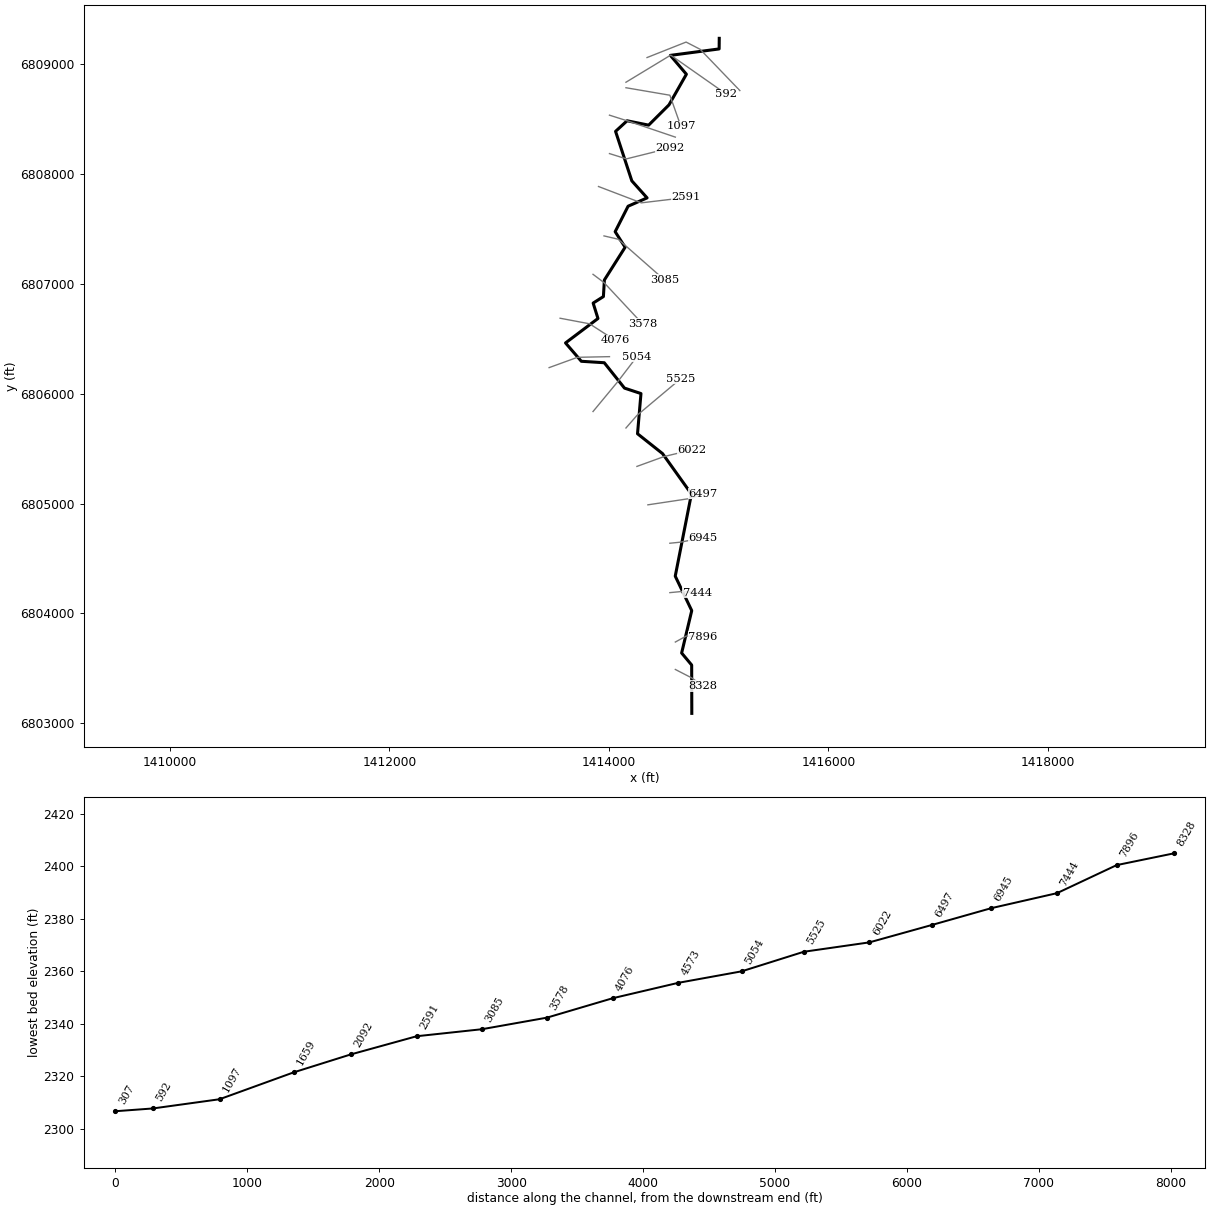
--- Holder Creek Trib4.prj (project) ---

Proj Title=Holder Creek Trib4 Base Level Engineering
Current Plan=p01
Default Exp/Contr=0.3,0.1
English Units
Geom File=g01
Flow File=f01
Plan File=p01
Y Axis Title=Elevation
X Axis Title(PF)=Main Channel Distance
X Axis Title(XS)=Station
BEGIN DESCRIPTION:
Holder Creek Trib4
END DESCRIPTION:
DSS Export Rating Curves= 0
DSS Export Rating Curve Sorted= 0
DSS Export Volume Flow Curves= 0
DXF OffsetX= 0
DXF OffsetY= 0
DXF ScaleX= 1
DXF ScaleY= 10

--- Holder Creek Trib4.p01 (plan) ---

Plan Title=Multiple Run
Short Identifier=Multiple
Geom File=g01
Flow File=f01
Subcritical Flow
K Sum by GR= 0
Std Step Tol= 0.01
Critical Tol= 0.01
Num of Std Step Trials= 20
Max Error Tol= 0.3
Flow Tol Ratio= 0.001
Split Flow NTrial= 30
Split Flow Tol= 0.02
Split Flow Ratio= 0.02
Log Output Level= 0
Friction Slope Method= 1
Unsteady Friction Slope Method= 2
Unsteady Bridges Friction Slope Method= 1
Parabolic Critical Depth
Global Vel Dist=  1 , 1 , 1
Global Log Level= 0
CheckData=True
Encroach Param= -1, 0, 0, 0
BEGIN DESCRIPTION:
Multiple Run
END DESCRIPTION:

--- Holder Creek Trib4.f01 (steady flow) ---

Flow Title=Multiple
Number of Profiles=7
Profile Names=10-year,25-year,50-year,1pct_min,100-year,1pct_plu,500-year
River Rch & RM= Holder Creek Tri,Reach-1,8328
     480     704     897     569    1135    2265    1841
Boundary for River Rch & Prof#=Holder Creek Tri,Reach-1,1
Up Type=0
Dn Type=3
Dn Slope=0.005
Boundary for River Rch & Prof#=Holder Creek Tri,Reach-1,2
Up Type=0
Dn Type=3
Dn Slope=0.005
Boundary for River Rch & Prof#=Holder Creek Tri,Reach-1,3
Up Type=0
Dn Type=3
Dn Slope=0.005
Boundary for River Rch & Prof#=Holder Creek Tri,Reach-1,4
Up Type=0
Dn Type=3
Dn Slope=0.005
Boundary for River Rch & Prof#=Holder Creek Tri,Reach-1,5
Up Type=0
Dn Type=3
Dn Slope=0.005
Boundary for River Rch & Prof#=Holder Creek Tri,Reach-1,6
Up Type=0
Dn Type=3
Dn Slope=0.005
Boundary for River Rch & Prof#=Holder Creek Tri,Reach-1,7
Up Type=0
Dn Type=3
Dn Slope=0.005

--- Holder Creek Trib4.g01 (geometry) ---

Geom Title=Existing Conditions

River Reach=Holder Creek Tri,Reach-1
Reach XY= 30
      1414755.00      6803088.00      1414753.78      6803528.41
      1414662.33      6803637.90      1414754.35      6804024.08
      1414604.08      6804338.34      1414751.47      6805086.52
      1414488.36      6805454.71      1414260.45      6805635.53
      1414291.84      6806001.72      1414141.67      6806051.39
      1413957.47      6806282.55      1413748.54      6806295.74
      1413604.53      6806462.93      1413900.01      6806685.46
      1413856.20      6806825.98      1413949.59      6806885.32
      1413958.56      6807036.53      1414147.39      6807334.67
      1414056.70      6807476.51      1414174.58      6807708.57
      1414347.53      6807784.38      1414208.54      6807939.47
      1414060.39      6808390.44      1414165.43      6808486.97
      1414361.74      6808447.13      1414547.14      6808631.83
      1414705.64      6808910.97      1414559.59      6809082.74
      1415003.97      6809141.48      1415005.00      6809238.00

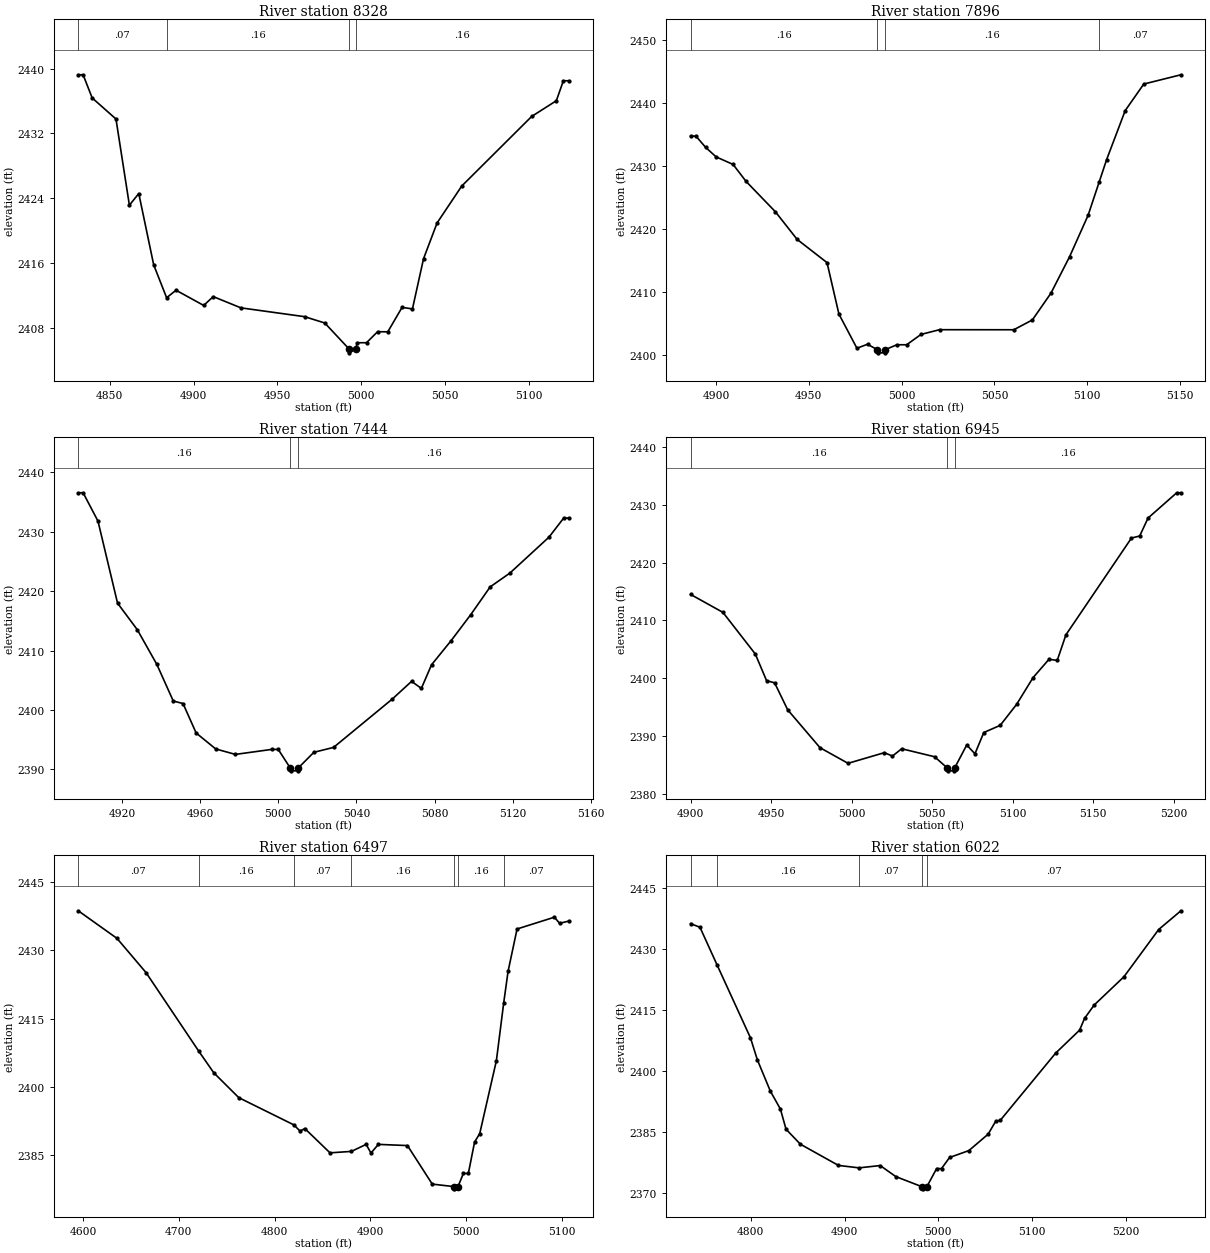
Type RM Length L Ch R = 1,8328,432,432,432
BEGIN DESCRIPTION:
Holder Creek Trib4 16.0
END DESCRIPTION:
XS GIS Cut Line= 3
      1414604.96      6803488.02      1414755.02      6803410.74
      1414854.97      6803338.02
#Sta/Elev= 30
  4831.2 2439.24  4834.1 2439.24  4839.5 2436.38  4853.7 2433.77  4861.7 2423.12
  4867.3 2424.56  4876.2 2415.74  4883.9 2411.68  4889.5 2412.61  4906.0 2410.73
  4911.7 2411.82  4928.2 2410.43  4966.2 2409.34  4978.2 2408.56  4992.6 2405.37
  4992.9 2404.87  4996.8 2405.37  4997.5 2406.12  5003.1 2406.12  5009.7 2407.48
  5015.8 2407.47  5024.3 2410.49  5030.5 2410.30  5037.1 2416.50  5045.2 2420.93
  5059.9 2425.49  5101.6 2434.09  5116.3 2436.03  5120.5 2438.50  5123.6 2438.50
#Mann=4,-1,0
  4831.2    0.07       0  4883.9    0.16       0  4992.6    0.07       0
  4996.8    0.16       0
Bank Sta=4992.6,4996.8
Exp/Cntr=0.3,0.1

Type RM Length L Ch R = 1,7896,452,452,452
BEGIN DESCRIPTION:
Holder Creek Trib4 15.0
END DESCRIPTION:
XS GIS Cut Line= 3
      1414604.96      6803737.98      1414704.62      6803792.70
      1414854.95      6803788.00
#Sta/Elev= 30
  4886.3 2434.78  4889.2 2434.78  4894.4 2433.00  4900.1 2431.48  4909.2 2430.29
  4916.2 2427.60  4932.0 2422.78  4943.7 2418.40  4959.8 2414.72  4966.2 2406.56
  4975.9 2401.14  4981.6 2401.77  4986.9 2400.91  4987.2 2400.41  4990.8 2400.41
  4991.1 2400.91  4997.4 2401.69  5002.7 2401.69  5010.4 2403.33  5020.4 2404.08
  5060.4 2404.07  5070.4 2405.63  5080.4 2409.87  5090.4 2415.63  5100.4 2422.21
  5106.4 2427.52  5110.4 2431.06  5120.4 2438.83  5130.4 2443.04  5150.4 2444.51
#Mann=4,-1,0
  4886.3    0.16       0  4986.9    0.07       0  4991.1    0.16       0
  5106.4    0.07       0
Bank Sta=4986.9,4991.1
Exp/Cntr=0.3,0.1

Type RM Length L Ch R = 1,7444,499,499,499
BEGIN DESCRIPTION:
Holder Creek Trib4 14.0
END DESCRIPTION:
XS GIS Cut Line= 3
      1414554.98      6804188.00      1414656.81      6804197.84
      1414804.98      6804188.00
#Sta/Elev= 30
  4897.7 2436.58  4900.2 2436.58  4907.8 2431.80  4917.8 2417.98  4927.9 2413.51
  4937.9 2407.66  4946.3 2401.49  4951.3 2401.06  4958.0 2396.10  4968.0 2393.41
  4978.1 2392.49  4996.6 2393.33  5000.0 2393.33  5006.1 2390.22  5006.4 2389.72
  5010.1 2389.72  5010.3 2390.22  5018.2 2392.84  5028.3 2393.67  5058.3 2401.81
  5068.2 2404.80  5073.2 2403.61  5078.4 2407.59  5088.4 2411.65  5098.4 2416.01
  5108.4 2420.72  5118.5 2423.05  5138.5 2429.11  5146.0 2432.32  5148.5 2432.32
#Mann=3,-1,0
  4897.7    0.16       0  5006.1    0.07       0  5010.3    0.16       0
Bank Sta=5006.1,5010.3
Exp/Cntr=0.3,0.1

Type RM Length L Ch R = 1,6945,448,448,448
BEGIN DESCRIPTION:
Holder Creek Trib4 13.0
END DESCRIPTION:
XS GIS Cut Line= 3
      1414554.97      6804638.00      1414654.55      6804648.19
      1414855.03      6804688.01
#Sta/Elev= 30
  4899.9 2414.51  4920.0 2411.40  4940.1 2404.20  4947.1 2399.59  4952.1 2399.21
  4960.2 2394.55  4980.3 2387.99  4997.7 2385.29  5020.2 2387.13  5025.3 2386.55
  5031.0 2387.81  5051.4 2386.43  5059.3 2384.49  5059.7 2383.99  5063.6 2383.99
  5063.9 2384.49  5071.4 2388.46  5076.5 2386.94  5082.0 2390.62  5092.2 2391.86
  5102.4 2395.50  5112.6 2400.12  5122.5 2403.29  5127.6 2403.09  5133.0 2407.52
  5173.7 2424.26  5178.8 2424.61  5184.0 2427.72  5201.8 2432.09  5204.4 2432.09
#Mann=3,-1,0
  4899.9    0.16       0  5059.3    0.07       0  5063.9    0.16       0
Bank Sta=5059.3,5063.9
Exp/Cntr=0.3,0.1

Type RM Length L Ch R = 1,6497,475,475,475
BEGIN DESCRIPTION:
Holder Creek Trib4 12.0
END DESCRIPTION:
XS GIS Cut Line= 3
      1414354.96      6804987.99      1414755.57      6805048.14
      1414854.98      6805087.99
#Sta/Elev= 30
  4594.9 2438.72  4635.4 2432.65  4665.7 2425.14  4720.6 2407.92  4736.5 2403.11
  4762.6 2397.65  4820.2 2391.66  4826.6 2390.30  4831.6 2390.86  4857.9 2385.52
  4880.3 2385.84  4895.6 2387.38  4900.7 2385.48  4908.4 2387.38  4938.8 2387.12
  4964.7 2378.65  4987.0 2378.11  4987.4 2377.61  4991.6 2378.11  4997.2 2380.99
  5002.4 2380.99  5008.9 2387.88  5014.3 2389.76  5031.7 2405.78  5039.3 2418.42
  5043.9 2425.41  5053.3 2434.72  5092.3 2437.31  5097.7 2435.97  5107.1 2436.44
#Mann=7,-1,0
  4594.9    0.07       0  4720.6    0.16       0  4820.2    0.07       0
  4880.3    0.16       0  4987.0    0.07       0  4991.6    0.16       0
  5039.3    0.07       0
Bank Sta=4987,4991.6
Exp/Cntr=0.3,0.1

Type RM Length L Ch R = 1,6022,497,497,497
BEGIN DESCRIPTION:
Holder Creek Trib4 11.0
END DESCRIPTION:
XS GIS Cut Line= 3
      1414254.98      6805337.99      1414503.30      6805428.21
      1414755.00      6805488.00
#Sta/Elev= 30
  4735.8 2436.19  4745.8 2435.31  4764.3 2425.92  4799.7 2408.09  4807.0 2402.71
  4820.9 2394.98  4831.6 2390.59  4837.6 2385.63  4852.9 2381.94  4893.5 2376.72
  4915.5 2376.12  4938.0 2376.69  4954.7 2373.97  4982.8 2371.46  4983.2 2370.96
  4987.7 2371.46  4998.2 2375.94  5003.4 2375.94  5012.0 2378.67  5032.6 2380.37
  5053.1 2384.40  5061.1 2387.55  5066.3 2387.87  5125.1 2404.34  5150.7 2410.01
  5155.9 2412.87  5166.2 2416.17  5198.0 2423.14  5235.0 2434.75  5258.7 2439.36
#Mann=5,-1,0
  4735.8    0.07       0  4764.3    0.16       0  4915.5    0.07       0
  4982.8    0.07       0  4987.7    0.07       0
Bank Sta=4982.8,4987.7
Exp/Cntr=0.3,0.1

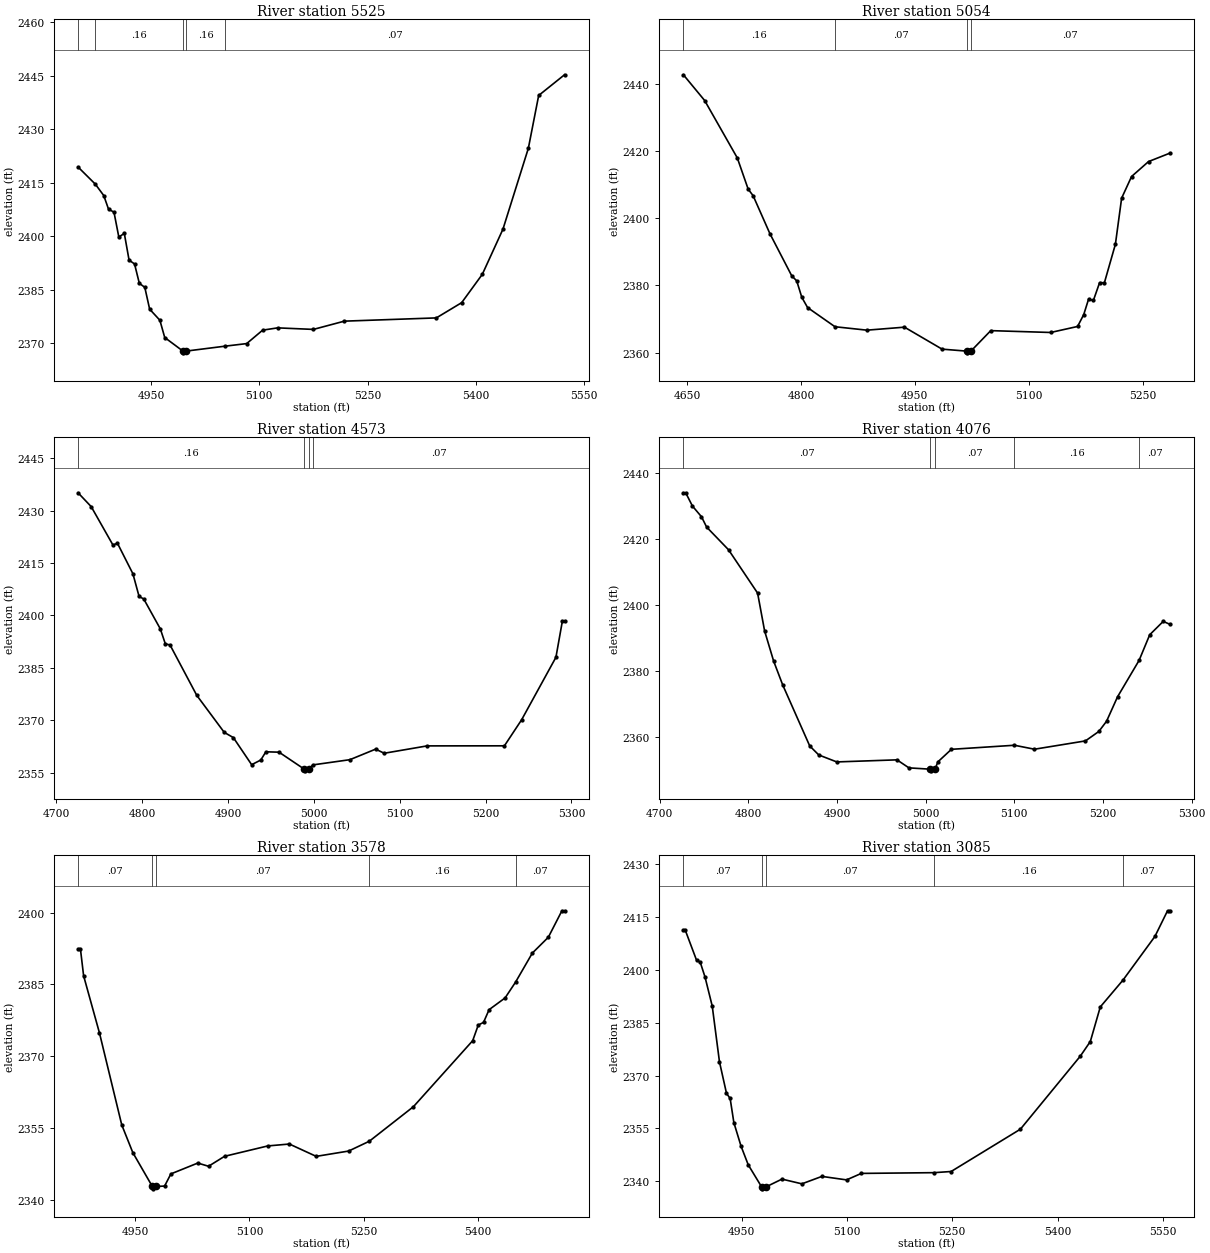
Type RM Length L Ch R = 1,5525,471,471,471
BEGIN DESCRIPTION:
Holder Creek Trib4 10.0
END DESCRIPTION:
XS GIS Cut Line= 3
      1414155.01      6805688.01      1414254.56      6805801.82
      1414655.04      6806138.03
#Sta/Elev= 30
  4848.8 2419.40  4872.7 2414.61  4884.4 2411.42  4891.0 2407.62  4898.6 2406.75
  4905.3 2399.79  4912.9 2400.82  4919.5 2393.33  4927.1 2392.26  4933.7 2386.85
  4941.3 2385.71  4948.0 2379.61  4962.2 2376.50  4968.9 2371.67  4994.1 2367.88
  4994.4 2367.38  4999.0 2367.88  5052.3 2369.24  5082.5 2369.97  5104.6 2373.73
  5125.4 2374.37  5174.9 2373.94  5217.8 2376.25  5345.3 2377.16  5380.4 2381.43
  5409.0 2389.36  5437.6 2402.00  5472.8 2424.65  5487.1 2439.43  5522.9 2445.22
#Mann=5,-1,0
  4848.8    0.07       0  4872.7    0.16       0  4994.1    0.07       0
  4999.0    0.16       0  5052.3    0.07       0
Bank Sta=4994.1,4999
Exp/Cntr=0.3,0.1

Type RM Length L Ch R = 1,5054,481,481,481
BEGIN DESCRIPTION:
Holder Creek Trib4 9.0
END DESCRIPTION:
XS GIS Cut Line= 3
      1413854.98      6805837.97      1414081.27      6806111.11
      1414255.02      6806338.03
#Sta/Elev= 30
  4645.3 2442.69  4673.3 2435.03  4716.3 2417.93  4730.6 2408.64  4737.1 2406.70
  4759.3 2395.35  4788.0 2382.83  4794.5 2381.35  4801.2 2376.45  4808.8 2373.40
  4844.9 2367.69  4886.9 2366.67  4936.4 2367.56  4985.9 2361.02  5018.8 2360.42
  5019.1 2359.92  5023.8 2360.42  5050.0 2366.53  5128.9 2365.98  5164.3 2367.77
  5172.4 2371.30  5178.8 2375.91  5185.1 2375.50  5193.3 2380.81  5199.6 2380.77
  5214.1 2392.24  5222.3 2405.96  5235.4 2412.41  5257.7 2416.85  5285.8 2419.36
#Mann=4,-1,0
  4645.3    0.16       0  4844.9    0.07       0  5018.8    0.07       0
  5023.8    0.07       0
Bank Sta=5018.8,5023.8
Exp/Cntr=0.3,0.1

Type RM Length L Ch R = 1,4573,497,497,497
BEGIN DESCRIPTION:
Holder Creek Trib4 8.0
END DESCRIPTION:
XS GIS Cut Line= 3
      1413455.00      6806238.00      1413713.14      6806331.92
      1414004.98      6806338.00
#Sta/Elev= 30
  4725.3 2435.10  4740.6 2431.14  4765.9 2420.17  4771.2 2420.65  4789.2 2411.92
  4796.4 2405.42  4801.8 2404.72  4821.1 2396.16  4827.0 2391.84  4832.4 2391.56
  4863.6 2377.12  4895.6 2366.53  4906.2 2365.04  4927.5 2357.29  4938.1 2358.62
  4944.1 2360.98  4959.4 2360.87  4988.7 2356.03  4989.1 2355.53  4994.0 2356.03
  4998.8 2357.23  5041.9 2358.72  5071.9 2361.74  5081.9 2360.56  5131.9 2362.67
  5221.9 2362.69  5241.9 2370.12  5281.9 2388.02  5289.4 2398.37  5291.9 2398.37
#Mann=4,-1,0
  4725.3    0.16       0  4988.7    0.07       0  4994.0    0.16       0
  4998.8    0.07       0
Bank Sta=4988.7,4994
Exp/Cntr=0.3,0.1

Type RM Length L Ch R = 1,4076,498,498,498
BEGIN DESCRIPTION:
Holder Creek Trib4 7.0
END DESCRIPTION:
XS GIS Cut Line= 3
      1413554.97      6806688.00      1413823.53      6806637.31
      1414054.96      6806488.03
#Sta/Elev= 30
  4726.7 2433.90  4729.3 2433.90  4736.9 2429.88  4747.1 2426.64  4752.9 2423.51
  4777.6 2416.64  4810.4 2403.51  4818.3 2392.05  4828.5 2382.90  4838.7 2375.70
  4869.2 2357.20  4879.4 2354.47  4899.7 2352.36  4967.6 2352.99  4981.1 2350.56
  5005.2 2350.16  5005.6 2349.66  5010.5 2350.16  5013.8 2352.39  5029.0 2356.18
  5100.1 2357.41  5122.7 2356.21  5180.2 2358.73  5195.3 2361.59  5204.0 2364.68
  5216.4 2372.09  5240.7 2383.12  5252.7 2390.89  5267.9 2394.93  5275.4 2394.06
#Mann=5,-1,0
  4726.7    0.07       0  5005.2    0.07       0  5010.5    0.07       0
  5100.1    0.16       0  5240.7    0.07       0
Bank Sta=5005.2,5010.5
Exp/Cntr=0.3,0.1

Type RM Length L Ch R = 1,3578,493,493,493
BEGIN DESCRIPTION:
Holder Creek Trib4 6.0
END DESCRIPTION:
XS GIS Cut Line= 3
      1413855.02      6807087.99      1413954.73      6807013.11
      1414304.99      6806638.01
#Sta/Elev= 30
  4875.3 2392.45  4878.4 2392.45  4882.6 2386.80  4903.4 2374.84  4932.6 2355.63
  4947.1 2349.84  4972.7 2342.76  4973.1 2342.26  4978.0 2342.76  4988.8 2342.84
  4997.0 2345.38  5032.3 2347.65  5046.4 2346.98  5067.4 2349.06  5124.1 2351.23
  5152.4 2351.63  5187.6 2349.05  5230.1 2350.16  5257.2 2352.21  5315.1 2359.44
  5392.8 2373.24  5400.1 2376.51  5407.0 2377.06  5414.3 2379.72  5435.3 2382.18
  5449.0 2385.48  5471.0 2391.55  5492.0 2394.87  5509.8 2400.40  5513.2 2400.40
#Mann=5,-1,0
  4875.3    0.07       0  4972.7    0.07       0  4978.0    0.07       0
  5257.2    0.16       0  5449.0    0.07       0
Bank Sta=4972.7,4978
Exp/Cntr=0.3,0.1

Type RM Length L Ch R = 1,3085,494,494,494
BEGIN DESCRIPTION:
Holder Creek Trib4 5.0
END DESCRIPTION:
XS GIS Cut Line= 3
      1413954.98      6807438.00      1414084.54      6807407.93
      1414504.97      6807038.02
#Sta/Elev= 30
  4867.0 2411.30  4869.6 2411.30  4885.8 2402.71  4890.9 2402.22  4897.8 2397.98
  4908.1 2389.71  4918.4 2373.89  4928.4 2364.96  4933.6 2363.50  4938.9 2356.65
  4949.1 2349.98  4959.4 2344.65  4978.6 2338.35  4979.0 2337.85  4984.1 2338.35
  5007.4 2340.61  5035.8 2339.27  5064.3 2341.38  5099.4 2340.39  5120.5 2342.23
  5224.0 2342.44  5248.4 2342.77  5347.1 2354.78  5432.4 2375.50  5446.7 2379.66
  5460.9 2389.48  5493.3 2397.11  5538.7 2409.48  5556.7 2416.77  5560.0 2416.77
#Mann=5,-1,0
  4867.0    0.07       0  4978.6    0.07       0  4984.1    0.07       0
  5224.0    0.16       0  5493.3    0.07       0
Bank Sta=4978.6,4984.1
Exp/Cntr=0.3,0.1

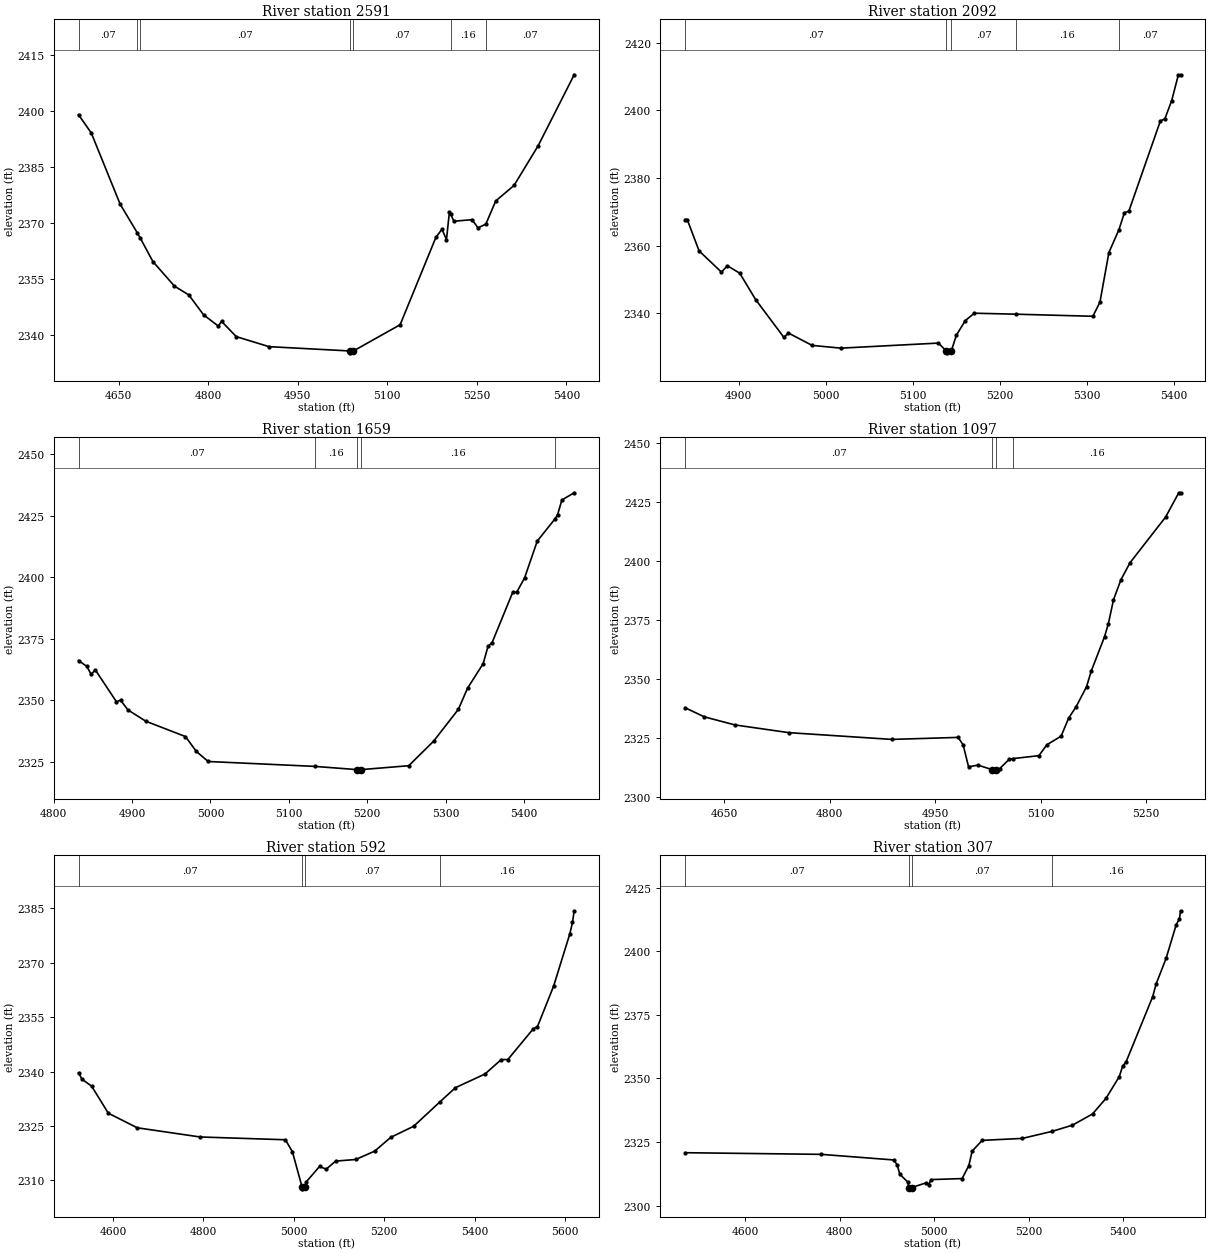
Type RM Length L Ch R = 1,2591,499,499,499
BEGIN DESCRIPTION:
Holder Creek Trib4 4.0
END DESCRIPTION:
XS GIS Cut Line= 3
      1413905.00      6807888.00      1414294.85      6807739.17
      1414704.96      6807788.00
#Sta/Elev= 30
  4582.7 2399.08  4604.1 2394.17  4652.5 2375.05  4681.0 2367.43  4686.5 2365.88
  4707.3 2359.68  4743.3 2353.10  4767.5 2350.71  4792.2 2345.38  4816.9 2342.36
  4822.3 2343.63  4847.0 2339.53  4901.8 2336.84  5037.6 2335.68  5038.1 2335.18
  5043.2 2335.68  5121.5 2342.73  5181.4 2366.17  5191.5 2368.33  5199.1 2365.59
  5204.1 2373.07  5206.0 2372.42  5211.6 2370.49  5241.8 2370.91  5251.9 2368.73
  5265.0 2369.71  5281.6 2375.93  5312.3 2380.11  5352.6 2390.72  5413.0 2409.79
#Mann=7,-1,0
  4582.7    0.07       0  4681.0    0.16       0  4686.5    0.07       0
  5037.6    0.07       0  5043.2    0.07       0  5206.0    0.16       0
  5265.0    0.07       0
Bank Sta=5037.6,5043.2
Exp/Cntr=0.3,0.1

Type RM Length L Ch R = 1,2092,433,433,433
BEGIN DESCRIPTION:
Holder Creek Trib4 3.0
END DESCRIPTION:
XS GIS Cut Line= 3
      1414004.99      6808188.00      1414159.22      6808139.75
      1414555.01      6808238.00
#Sta/Elev= 30
  4838.4 2367.69  4841.0 2367.69  4854.6 2358.43  4880.3 2352.14  4887.1 2354.03
  4901.3 2351.82  4919.6 2344.00  4952.0 2332.84  4957.3 2334.10  4984.5 2330.45
  5017.5 2329.64  5129.6 2331.14  5138.7 2328.75  5139.2 2328.25  5144.3 2328.75
  5150.2 2333.49  5160.5 2337.81  5170.8 2339.98  5218.3 2339.69  5307.0 2339.07
  5315.1 2343.25  5325.4 2357.94  5337.0 2364.75  5343.2 2369.73  5348.3 2370.18
  5384.5 2396.87  5389.7 2397.53  5397.5 2402.89  5405.2 2410.55  5407.8 2410.55
#Mann=5,-1,0
  4838.4    0.07       0  5138.7    0.07       0  5144.3    0.07       0
  5218.3    0.16       0  5337.0    0.07       0
Bank Sta=5138.7,5144.3
Exp/Cntr=0.3,0.1

Type RM Length L Ch R = 1,1659,562,562,562
BEGIN DESCRIPTION:
Holder Creek Trib4 2.0
END DESCRIPTION:
XS GIS Cut Line= 3
      1414004.96      6808538.01      1414165.43      6808486.97
      1414604.98      6808338.01
#Sta/Elev= 30
  4831.6 2366.17  4842.1 2363.81  4847.8 2360.57  4853.0 2362.39  4880.0 2349.43
  4885.2 2350.09  4894.6 2346.15  4917.5 2341.54  4968.1 2335.32  4982.0 2329.27
  4997.1 2325.20  5132.9 2323.22  5186.8 2321.91  5187.2 2321.41  5192.4 2321.91
  5253.0 2323.49  5284.6 2333.39  5316.3 2346.35  5328.0 2354.91  5348.0 2364.92
  5354.2 2371.97  5359.4 2373.48  5385.6 2393.77  5390.9 2393.94  5400.8 2399.67
  5417.0 2414.64  5439.5 2423.58  5443.0 2425.40  5448.4 2431.30  5464.1 2434.23
#Mann=5,-1,0
  4831.6    0.07       0  5132.9    0.16       0  5186.8    0.07       0
  5192.4    0.16       0  5439.5    0.07       0
Bank Sta=5186.8,5192.4
Exp/Cntr=0.3,0.1

Type RM Length L Ch R = 1,1097,505,505,505
BEGIN DESCRIPTION:
Holder Creek Trib4 1.0
END DESCRIPTION:
XS GIS Cut Line= 3
      1414155.04      6808787.99      1414555.25      6808719.71
      1414655.02      6808437.95
#Sta/Elev= 30
  4594.0 2337.94  4621.5 2334.05  4665.0 2330.63  4741.8 2327.35  4888.2 2324.49
  4982.5 2325.34  4989.6 2322.16  4997.3 2312.87  5010.7 2313.59  5030.8 2311.66
  5031.2 2311.16  5036.5 2311.66  5041.6 2312.11  5054.9 2316.00  5060.7 2316.36
  5097.3 2317.59  5108.7 2322.22  5128.9 2325.86  5139.7 2333.53  5150.3 2338.37
  5165.1 2346.83  5171.6 2353.32  5190.7 2368.06  5196.0 2373.37  5203.4 2383.68
  5214.0 2392.20  5226.9 2399.40  5277.6 2418.80  5296.2 2429.07  5298.9 2429.07
#Mann=4,-1,0
  4594.0    0.07       0  5030.8    0.07       0  5036.5    0.07       0
  5060.7    0.16       0
Bank Sta=5030.8,5036.5
Exp/Cntr=0.3,0.1

Type RM Length L Ch R = 1,592,285,285,285
BEGIN DESCRIPTION:
Holder Creek Trib4 1482
END DESCRIPTION:
XS GIS Cut Line= 3
      1414154.98      6808837.99      1414562.55      6809084.84
      1415070.37      6808728.97
#Sta/Elev= 30
  4523.5 2339.65  4531.3 2337.89  4552.6 2335.96  4589.5 2328.51  4653.5 2324.49
  4792.4 2321.96  4981.2 2321.19  4996.7 2317.90  5018.1 2308.15  5018.6 2307.65
  5023.8 2308.15  5027.4 2309.57  5056.7 2313.82  5071.5 2313.08  5092.4 2315.30
  5136.9 2315.75  5178.7 2318.05  5214.5 2321.87  5265.0 2324.91  5323.0 2331.63
  5357.5 2335.56  5422.8 2339.33  5458.6 2343.29  5473.4 2343.33  5530.1 2351.87
  5538.8 2352.37  5574.5 2363.53  5610.3 2377.91  5616.4 2381.15  5620.1 2384.36
#Mann=4,-1,0
  4523.5    0.07       0  5018.1    0.07       0  5023.8    0.07       0
  5323.0    0.16       0
Bank Sta=5018.1,5023.8
Exp/Cntr=0.3,0.1

Type RM Length L Ch R = 1,307,0,0,0
BEGIN DESCRIPTION:
Holder Creek Trib4 4466
END DESCRIPTION:
XS GIS Cut Line= 4
      1414347.04      6809062.96      1414702.97      6809204.03
      1414831.00      6809138.04      1415192.62      6808762.15
#Sta/Elev= 30
  4473.1 2320.80  4761.3 2320.15  4914.5 2317.95  4921.9 2316.04  4927.5 2312.35
  4944.1 2309.32  4946.8 2307.09  4947.3 2306.59  4952.5 2307.09  4982.0 2308.87
  4988.4 2308.25  4994.0 2310.23  5059.4 2310.62  5073.5 2315.72  5080.7 2321.46
  5101.8 2325.65  5186.7 2326.42  5249.7 2329.19  5292.7 2331.62  5335.2 2336.04
  5363.5 2342.12  5391.8 2350.71  5399.0 2354.88  5405.9 2356.38  5462.5 2382.16
  5469.7 2387.13  5490.8 2397.19  5512.2 2410.41  5519.1 2412.87  5521.6 2415.93
#Mann=4,-1,0
  4473.1    0.07       0  4946.8    0.07       0  4952.5    0.07       0
  5249.7    0.16       0
Bank Sta=4946.8,4952.5
Exp/Cntr=0.3,0.1

Chan Stop Cuts=-1