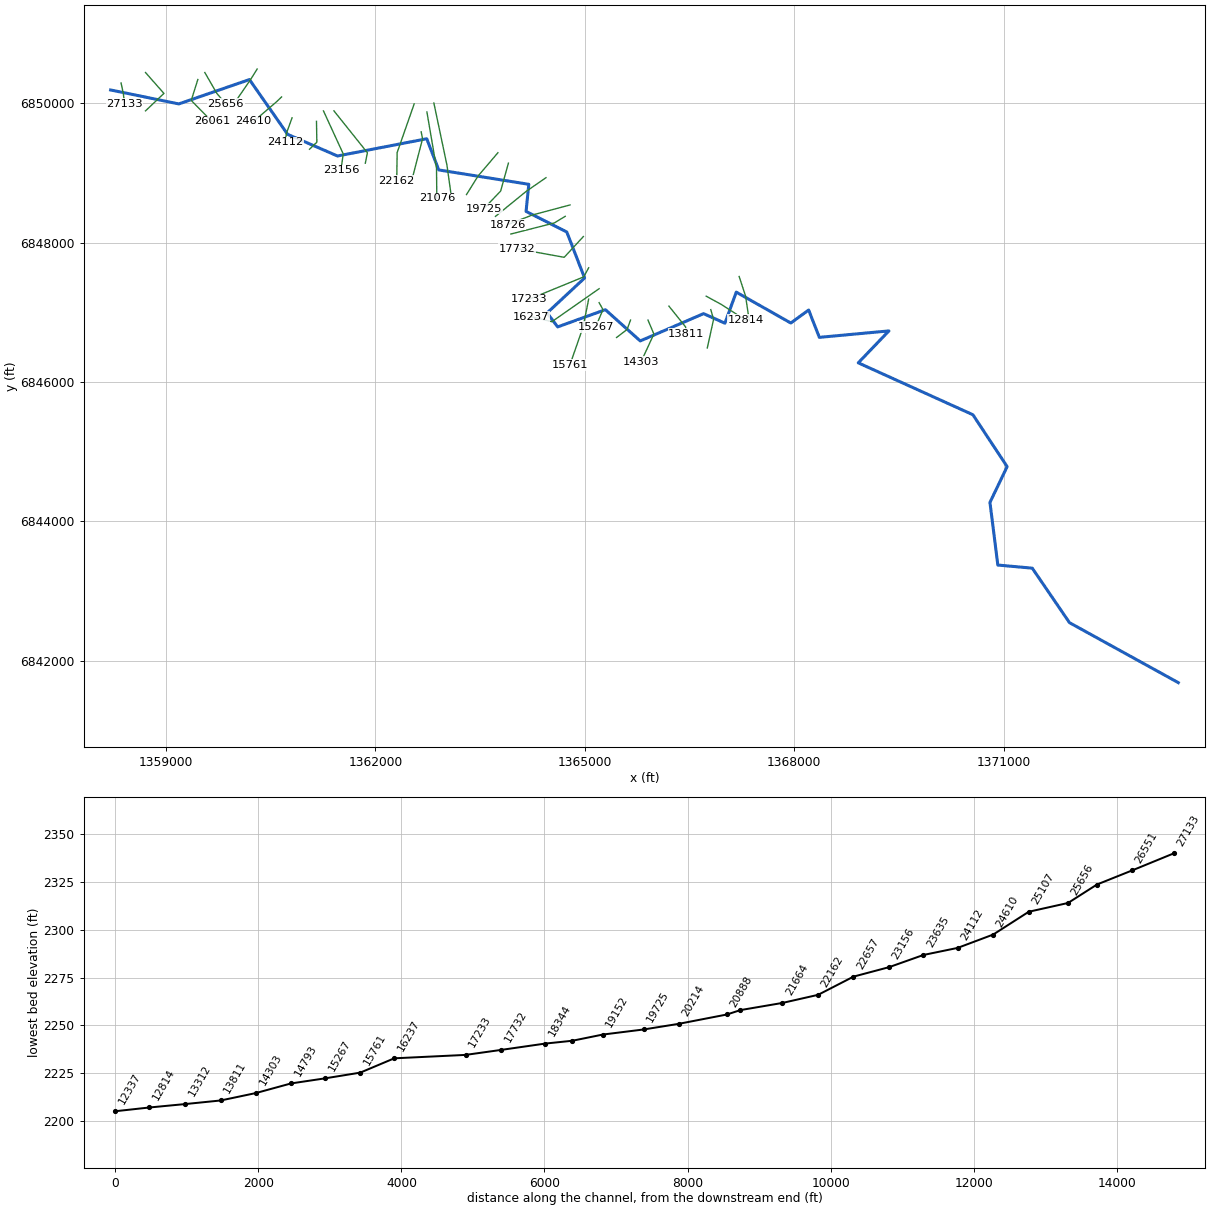
--- Idlewild Creek.prj (project) ---

Proj Title=Idlewild Creek Base Level Engineering
Current Plan=p01
Default Exp/Contr=0.3,0.1
English Units
Geom File=g01
Flow File=f01
Plan File=p01
Y Axis Title=Elevation
X Axis Title(PF)=Main Channel Distance
X Axis Title(XS)=Station
BEGIN DESCRIPTION:
Idlewild Creek
END DESCRIPTION:
DSS Export Rating Curves= 0
DSS Export Rating Curve Sorted= 0
DSS Export Volume Flow Curves= 0
DXF OffsetX= 0
DXF OffsetY= 0
DXF ScaleX= 1
DXF ScaleY= 10

--- Idlewild Creek.p01 (plan) ---

Plan Title=Multiple Run
Short Identifier=Multiple
Geom File=g01
Flow File=f01
Subcritical Flow
K Sum by GR= 0
Std Step Tol= 0.01
Critical Tol= 0.01
Num of Std Step Trials= 20
Max Error Tol= 0.3
Flow Tol Ratio= 0.001
Split Flow NTrial= 30
Split Flow Tol= 0.02
Split Flow Ratio= 0.02
Log Output Level= 0
Friction Slope Method= 1
Unsteady Friction Slope Method= 2
Unsteady Bridges Friction Slope Method= 1
Parabolic Critical Depth
Global Vel Dist=  1 , 1 , 1
Global Log Level= 0
CheckData=True
Encroach Param= -1, 0, 0, 0
BEGIN DESCRIPTION:
Multiple Run
END DESCRIPTION:

--- Idlewild Creek.f01 (steady flow) ---

Flow Title=Multiple
Program Version=4.10
Number of Profiles= 7
Profile Names=10-year,25-year,50-year,1pct_min,100-year,1pct_plu,500-year
River Rch & RM=Idlewild Creek,Reach-1         ,27133
     183     257     319     197     394     785     608
River Rch & RM=Idlewild Creek,Reach-1         ,22162
     450     659     839     530    1058    2112    1710
River Rch & RM=Idlewild Creek,Reach-1         ,15267
     459     672     856     541    1079    2153    1742
River Rch & RM=Idlewild Creek,Reach-1         ,12337
     537     789    1008     639    1274    2543    2066
River Rch & RM=Idlewild Creek,Reach-1         ,6457
     634     932    1192     755    1507    3007    2443
Boundary for River Rch & Prof#=Idlewild Creek,Reach-1         , 1
Up Type= 0
Dn Type= 3
Dn Slope=0.021
Boundary for River Rch & Prof#=Idlewild Creek,Reach-1         , 2
Up Type= 0
Dn Type= 3
Dn Slope=0.021
Boundary for River Rch & Prof#=Idlewild Creek,Reach-1         , 3
Up Type= 0
Dn Type= 3
Dn Slope=0.021
Boundary for River Rch & Prof#=Idlewild Creek,Reach-1         , 4
Up Type= 0
Dn Type= 3
Dn Slope=0.021
Boundary for River Rch & Prof#=Idlewild Creek,Reach-1         , 5
Up Type= 0
Dn Type= 3
Dn Slope=0.021
Boundary for River Rch & Prof#=Idlewild Creek,Reach-1         , 6
Up Type= 0
Dn Type= 3
Dn Slope=0.021
Boundary for River Rch & Prof#=Idlewild Creek,Reach-1         , 7
Up Type= 0
Dn Type= 3
Dn Slope=0.021
DSS Import GetInterval= 0
DSS Import GetPeak= 0
DSS Import FillOption= 0

--- Idlewild Creek.g01 (geometry) ---

Geom Title=Existing Conditions
Program Version=4.10

River Reach=Idlewild Creek  ,Reach-1
Reach XY= 30
        1358205.        6850188.      1359182.22      6849987.71
      1360194.45      6850336.92      1360741.67      6849551.39
      1361456.43      6849241.06      1362734.74      6849488.14
      1362906.65       6849041.1      1364197.46      6848834.94
      1364158.19      6848446.35      1364741.64      6848151.34
      1364996.92       6847491.3      1364459.95      6846990.57
      1364610.85      6846790.06      1365294.56      6847036.95
       1365794.3       6846588.7      1366701.69      6846979.98
      1367007.86      6846843.08      1367170.16      6847288.48
      1367951.78      6846845.83      1368207.55      6847032.28
      1368360.84      6846640.05      1369357.74      6846732.66
      1368918.37      6846274.68      1370561.21       6845530.2
      1371051.66      6844786.28      1370805.37      6844272.83
      1370918.36      6843374.65      1371411.48      6843330.31
       1371945.2      6842548.48        1373505.        6841688.

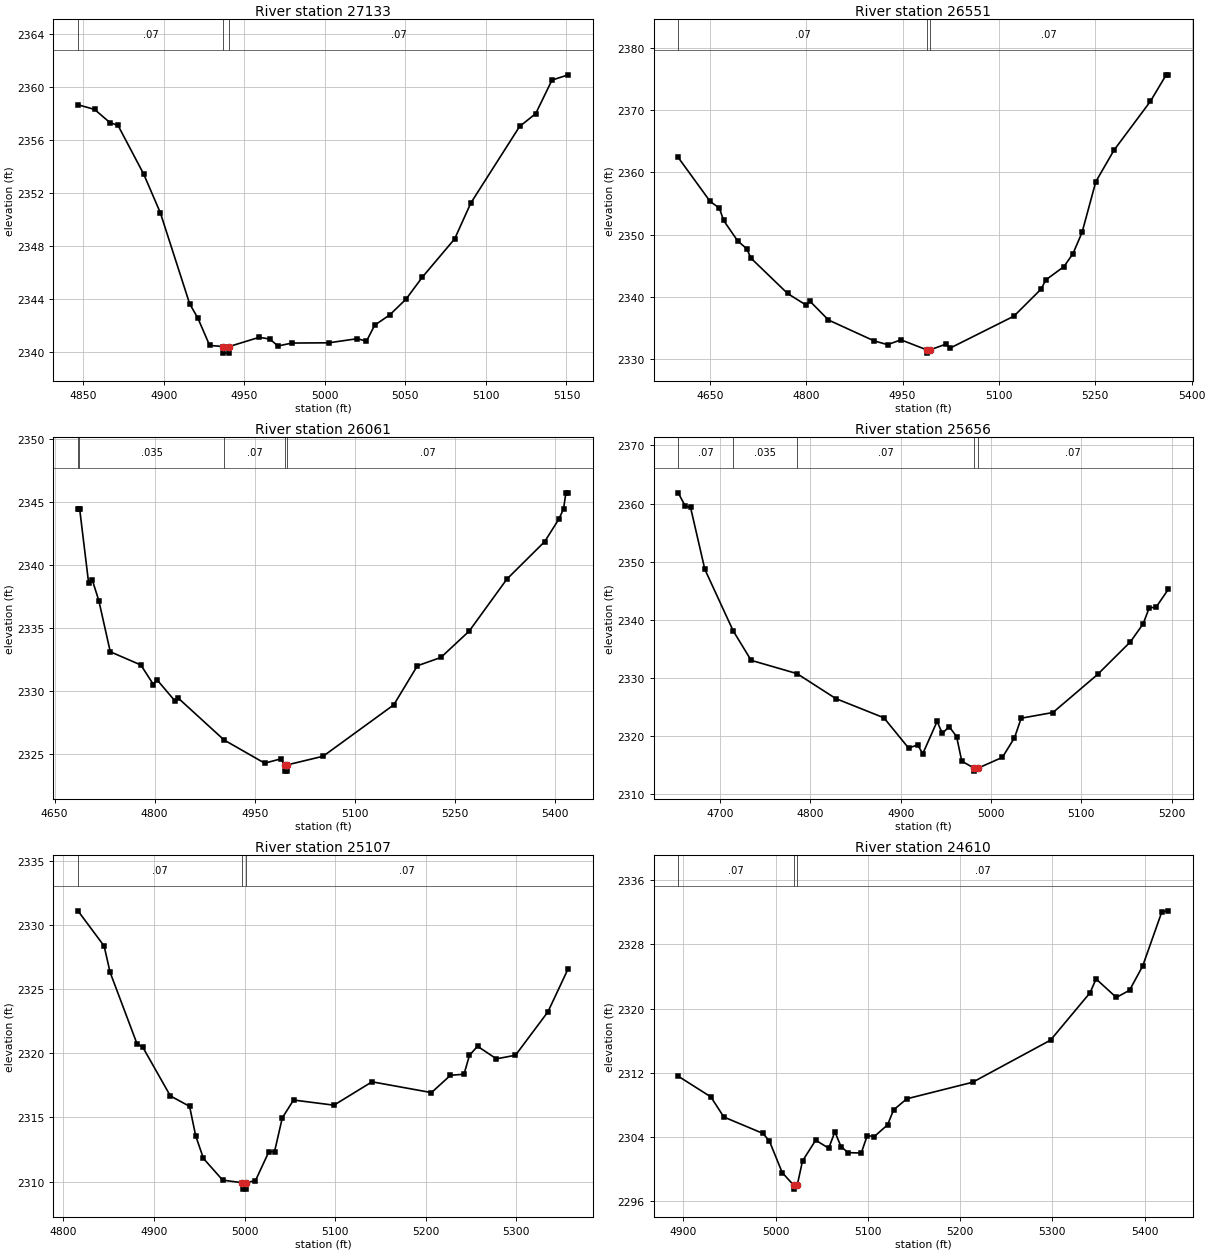
Type RM Length L Ch R = 1 ,27133   ,582,582,582
BEGIN DESCRIPTION:
Idlewild Creek 50.0
END DESCRIPTION:
XS GIS Cut Line= 3
      1358354.99      6850288.05      1358386.81      6850137.98
        1358405.      6849987.98
#Sta/Elev= 30
  4846.6 2358.68  4856.9 2358.33  4866.4 2357.34  4871.5 2357.12  4887.5 2353.43
  4897.8 2350.52    4916 2343.65  4921.1 2342.57  4928.4 2340.51  4936.6 2340.43
  4936.9 2339.93  4940.4 2339.93  4940.6 2340.43  4959.1 2341.12  4965.7    2341
  4970.8 2340.47  4979.5 2340.69  5002.5 2340.71  5020.1 2341.02  5025.8 2340.83
  5030.9 2342.04  5040.3 2342.82  5050.4 2344.01  5060.4 2345.65  5080.6 2348.56
  5090.6 2351.26  5120.9 2357.04  5130.9 2358.01    5141 2360.54  5151.1 2360.94
#Mann= 3 ,-1 , 0
  4846.6     .07       0  4936.6     .07       0  4940.6     .07       0
Bank Sta=4936.6,4940.6
XS Rating Curve= 0 ,0
Exp/Cntr=0.3,0.1

Type RM Length L Ch R = 1 ,26551   ,490,490,490
BEGIN DESCRIPTION:
Idlewild Creek 49.0
END DESCRIPTION:
XS GIS Cut Line= 3
      1358704.97      6850438.03       1358968.9      6850138.52
      1358704.98      6849887.98
#Sta/Elev= 30
  4600.8 2362.38  4650.6 2355.32  4664.9 2354.26  4671.5 2352.28  4693.3 2349.01
  4707.5 2347.74  4714.2 2346.22  4771.1 2340.57  4799.6 2338.73  4806.2  2339.3
  4834.7 2336.32  4905.8 2332.97  4926.7 2332.37  4947.6 2333.14  4988.3 2331.51
  4988.5 2331.01  4992.3 2331.51  5017.4 2332.45  5024.3 2331.83  5123.4 2336.94
  5165.9  2341.3  5172.8 2342.73  5201.1 2344.87  5215.2 2346.94  5229.4 2350.36
  5250.8 2358.49  5279.1 2363.54  5335.7 2371.36  5360.4 2375.62  5363.9 2375.62
#Mann= 3 ,-1 , 0
  4600.8     .07       0  4988.3     .07       0  4992.3     .07       0
Bank Sta=4988.3,4992.3
XS Rating Curve= 0 ,0
Exp/Cntr=0.3,0.1

Type RM Length L Ch R = 1 ,26061   ,405,405,405
BEGIN DESCRIPTION:
Idlewild Creek 48.0
END DESCRIPTION:
XS GIS Cut Line= 3
      1359454.99      6850337.97      1359360.17      6850037.58
      1359654.98      6849738.02
#Sta/Elev= 30
    4685 2344.47  4686.3 2344.47  4687.6 2344.47  4701.1 2338.57  4706.4 2338.86
  4716.4 2337.18  4733.5 2333.14  4779.4 2332.09  4798.2 2330.54  4803.4 2330.93
  4830.5 2329.24  4835.7 2329.45  4904.2 2326.14  4965.1  2324.3  4989.1 2324.64
  4995.2 2324.17  4995.4 2323.67  4998.9 2323.67  4999.2 2324.17  5052.7 2324.85
  5158.7 2328.93  5194.1 2332.03  5229.4 2332.69  5271.8 2334.78  5328.4 2338.91
    5385 2341.88  5406.2 2343.66  5413.3 2344.47  5416.8 2345.75  5420.3 2345.75
#Mann= 5 ,-1 , 0
    4685     .07       0  4686.3    .035       0  4904.2     .07       0
  4995.2     .07       0  4999.2     .07       0
Bank Sta=4995.2,4999.2
XS Rating Curve= 0 ,0
Exp/Cntr=0.3,0.1

Type RM Length L Ch R = 1 ,25656   ,549,549,549
BEGIN DESCRIPTION:
Idlewild Creek 47.0
END DESCRIPTION:
XS GIS Cut Line= 3
      1359554.99      6850438.02       1359727.8      6850137.81
      1359854.98      6849988.02
#Sta/Elev= 30
  4653.6 2361.86  4661.5 2359.56  4667.3 2359.35  4683.1 2348.71  4714.5 2338.13
  4734.4 2333.06  4785.1 2330.78  4828.2 2326.48  4881.4 2323.18  4908.7 2317.98
  4918.7 2318.51  4924.5 2317.02  4940.3 2322.56  4946.1 2320.49  4953.6 2321.67
  4961.9 2319.95  4967.6 2315.73  4981.4 2314.51  4981.7 2314.01  4985.4 2314.51
  5012.6 2316.38    5026 2319.74  5033.4 2323.11  5068.6 2324.09    5118 2330.63
  5154.3 2336.23  5168.5 2339.34  5175.1 2342.07  5182.8  2342.2  5196.5 2345.31
#Mann= 5 ,-1 , 0
  4653.6     .07       0  4714.5    .035       0  4785.1     .07       0
  4981.4     .07       0  4985.4     .07       0
Bank Sta=4981.4,4985.4
XS Rating Curve= 0 ,0
Exp/Cntr=0.3,0.1

Type RM Length L Ch R = 1 ,25107   ,497,497,497
BEGIN DESCRIPTION:
Idlewild Creek 46.0
END DESCRIPTION:
XS GIS Cut Line= 3
      1360305.02      6850488.04      1360207.32      6850332.36
      1360004.99      6850037.99
#Sta/Elev= 30
  4816.2  2331.1  4845.1 2328.36  4851.7 2326.31  4881.6  2320.7  4887.5 2320.51
  4918.2 2316.68  4939.4 2315.87  4946.1 2313.58  4954.7 2311.81  4975.9 2310.12
  4997.6 2309.92  4997.9 2309.42  5001.4 2309.42  5001.6 2309.92  5012.1 2310.08
    5027 2312.35  5033.1 2312.33  5041.7 2314.97  5054.1 2316.36  5098.7 2315.96
  5140.7 2317.78  5206.3 2316.94  5227.3 2318.29  5242.2 2318.37  5248.2 2319.84
  5257.1 2320.55    5278 2319.57    5299 2319.85  5334.8 2323.23  5357.2  2326.6
#Mann= 3 ,-1 , 0
  4816.2     .07       0  4997.6     .07       0  5001.6     .07       0
Bank Sta=4997.6,5001.6
XS Rating Curve= 0 ,0
Exp/Cntr=0.3,0.1

Type RM Length L Ch R = 1 ,24610   ,498,498,498
BEGIN DESCRIPTION:
Idlewild Creek 45.0
END DESCRIPTION:
XS GIS Cut Line= 3
      1360654.99      6850087.99      1360578.71      6850014.82
      1360255.02      6849738.02
#Sta/Elev= 30
  4894.3 2311.58  4929.7    2309  4943.8 2306.49  4986.3 2304.44  4993.2 2303.49
  5007.1 2299.56  5019.4    2298  5019.7  2297.5  5023.4    2298  5029.1 2301.01
  5043.4  2303.6  5057.5  2302.6  5064.2 2304.64  5070.8 2302.81  5078.5 2302.05
  5092.8    2302  5099.3 2304.17    5107 2304.06  5121.3 2305.51  5127.9 2307.38
  5142.2 2308.76  5213.5 2310.82    5298 2316.07  5340.9 2321.98  5347.4  2323.7
  5369.4 2321.39  5383.7 2322.29  5397.9  2325.3  5418.8 2332.09  5425.9 2332.19
#Mann= 3 ,-1 , 0
  4894.3     .07       0  5019.4     .07       0  5023.4     .07       0
Bank Sta=5019.4,5023.4
XS Rating Curve= 0 ,0
Exp/Cntr=0.3,0.1

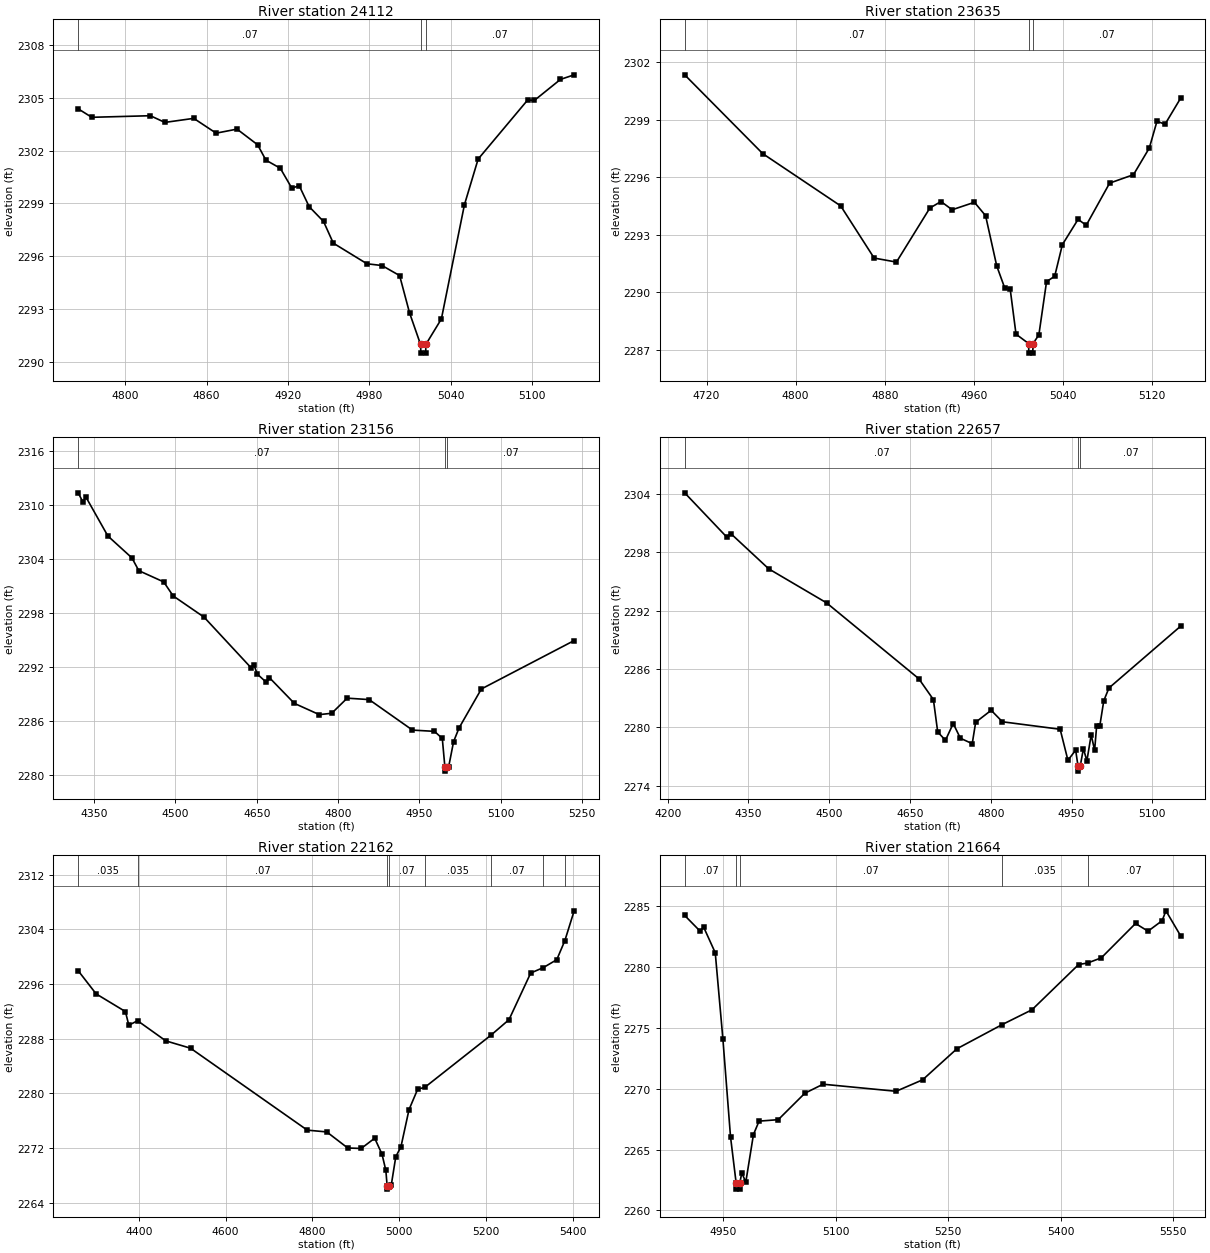
Type RM Length L Ch R = 1 ,24112   ,477,477,477
BEGIN DESCRIPTION:
Idlewild Creek 44.0
END DESCRIPTION:
XS GIS Cut Line= 3
      1360805.01      6849788.02      1360724.72      6849567.48
        1360705.      6849437.98
#Sta/Elev= 30
  4765.3 2304.37  4775.3 2303.89  4818.5 2303.98  4829.2  2303.6  4850.5 2303.83
    4867 2302.99  4882.4 2303.22  4897.6 2302.33  4903.7 2301.46  4914.3    2301
  4922.9 2299.86  4928.2 2300.02  4935.6 2298.82  4946.2 2297.98  4953.4 2296.75
  4978.2 2295.58  4989.3 2295.48  5002.3 2294.91  5009.6  2292.8  5017.7 2291.01
    5018 2290.51  5021.5 2290.51  5021.7 2291.01  5033.1 2292.45  5050.1 2298.93
  5060.2 2301.52  5096.7 2304.87  5101.7 2304.85  5120.9 2306.04    5131  2306.3
#Mann= 3 ,-1 , 0
  4765.3     .07       0  5017.7     .07       0  5021.7     .07       0
Bank Sta=5017.7,5021.7
XS Rating Curve= 0 ,0
Exp/Cntr=0.3,0.1

Type RM Length L Ch R = 1 ,23635   ,479,479,479
BEGIN DESCRIPTION:
Idlewild Creek 43.0
END DESCRIPTION:
XS GIS Cut Line= 3
        1361155.      6849737.99      1361160.18      6849438.44
      1361055.02      6849338.02
#Sta/Elev= 30
  4700.4 2301.35  4770.4 2297.24  4840.4 2294.51  4870.4 2291.79  4890.4 2291.58
  4920.4  2294.4  4930.4 2294.74  4940.4 2294.31  4960.4  2294.7  4970.4    2294
  4980.4 2291.38  4987.5 2290.24  4992.5 2290.16  4997.7 2287.82    5009 2287.33
  5009.2 2286.83  5012.7 2286.83    5013 2287.33  5018.2 2287.78  5025.1 2290.56
  5032.4 2290.84  5039.3 2292.49  5053.4 2293.81  5060.7  2293.5  5081.7  2295.7
  5103.1 2296.14  5117.3 2297.53  5124.2 2298.93  5131.4 2298.77  5145.4 2300.13
#Mann= 3 ,-1 , 0
  4700.4     .07       0    5009     .07       0    5013     .07       0
Bank Sta=5009,5013
XS Rating Curve= 0 ,0
Exp/Cntr=0.3,0.1

Type RM Length L Ch R = 1 ,23156   ,499,499,499
BEGIN DESCRIPTION:
Idlewild Creek 42.0
END DESCRIPTION:
XS GIS Cut Line= 3
        1361255.        6849888.      1361538.49      6849270.79
        1361505.      6849037.99
#Sta/Elev= 30
  4320.8  2311.4  4329.5 2310.37    4335 2310.93  4375.5  2306.6  4419.8 2304.17
  4432.5 2302.75  4478.4  2301.5  4495.9 2299.94  4552.9 2297.58  4639.3 2291.97
  4644.8 2292.28  4650.9 2291.26  4667.8 2290.33  4673.3 2290.86  4719.3    2288
  4765.3 2286.75  4788.2  2286.9  4816.7 2288.58  4857.2 2288.42  4937.1 2285.03
  4977.6 2284.89  4992.1  2284.1  4996.8 2280.97    4997 2280.47  5000.8 2280.97
  5003.9 2280.97  5012.9 2283.75    5023 2285.27  5064.1  2289.6  5235.2 2294.98
#Mann= 3 ,-1 , 0
  4320.8     .07       0  4996.8     .07       0  5000.8     .07       0
Bank Sta=4996.8,5000.8
XS Rating Curve= 0 ,0
Exp/Cntr=0.3,0.1

Type RM Length L Ch R = 1 ,22657   ,495,495,495
BEGIN DESCRIPTION:
Idlewild Creek 41.0
END DESCRIPTION:
XS GIS Cut Line= 3
      1361404.99      6849888.01      1361884.64      6849287.58
        1361855.      6849137.99
#Sta/Elev= 30
  4231.5 2304.09  4309.2 2299.57  4317.2  2299.9  4387.6 2296.28  4494.9 2292.79
  4666.2    2285  4693.4 2282.85  4701.4 2279.52  4715.8 2278.67  4730.2 2280.39
  4743.5 2278.88  4765.5 2278.32  4771.9 2280.52  4800.7 2281.75  4821.5 2280.57
  4928.8  2279.8  4943.2 2276.62  4957.6 2277.65    4962    2276  4962.2  2275.5
    4966    2276    4972 2277.82  4978.4 2276.55  4986.4 2279.22  4992.8 2277.64
  4996.5 2280.11  5002.3 2280.11  5009.8 2282.73  5019.4 2284.04  5152.5 2290.39
#Mann= 3 ,-1 , 0
  4231.5     .07       0    4962     .07       0    4966     .07       0
Bank Sta=4962,4966
XS Rating Curve= 0 ,0
Exp/Cntr=0.3,0.1

Type RM Length L Ch R = 1 ,22162   ,498,498,498
BEGIN DESCRIPTION:
Idlewild Creek 40.0
END DESCRIPTION:
XS GIS Cut Line= 3
      1362554.99      6849987.98      1362310.93      6849290.24
        1362305.      6848887.98
#Sta/Elev= 30
  4260.8 2297.93    4302 2294.55  4369.4 2291.96  4377.3 2289.96  4397.4 2290.62
  4462.5 2287.67  4519.3  2286.6    4788 2274.61  4832.9 2274.35  4881.1    2272
  4912.1 2271.93  4943.2 2273.43    4960  2271.1  4968.9 2268.71  4971.8 2266.48
  4972.1 2265.98  4976.7 2266.48  4981.2 2266.52  4991.8 2270.73  5003.6 2272.17
  5022.2 2277.61  5042.2 2280.61  5058.3 2280.86  5210.9 2288.51  5252.3 2290.77
  5302.3  2297.6  5331.3 2298.39  5362.3 2299.55  5380.9 2302.34  5402.3  2306.7
#Mann= 8 ,-1 , 0
  4260.8    .035       0  4397.4     .07       0  4971.8     .07       0
  4976.7     .07       0  5058.3    .035       0  5210.9     .07       0
  5331.3    .035       0  5380.9     .07       0
Bank Sta=4971.8,4976.7
XS Rating Curve= 0 ,0
Exp/Cntr=0.3,0.1

Type RM Length L Ch R = 1 ,21664   ,588,588,588
BEGIN DESCRIPTION:
Idlewild Creek 39.0
END DESCRIPTION:
XS GIS Cut Line= 3
        1362655.      6849588.02       1362675.1      6849488.33
       1362534.6      6848945.93
#Sta/Elev= 30
  4898.3 2284.21  4918.6 2282.94  4923.7 2283.24  4939.1 2281.15  4949.3 2274.08
  4959.5 2266.04    4967 2262.25  4967.3 2261.75  4971.5 2261.75  4971.9 2262.25
  4974.5 2263.08  4979.9 2262.33  4990.1 2266.23  4997.6 2267.33  5023.2 2267.45
  5058.7 2269.62    5083 2270.36  5180.5 2269.78  5215.9 2270.72  5261.7 2273.27
  5322.3 2275.26  5361.9 2276.47  5424.1 2280.18  5436.2 2280.31  5454.4 2280.73
  5500.1 2283.55  5516.8 2282.92  5535.6 2283.78  5540.7 2284.59  5560.3 2282.54
#Mann= 5 ,-1 , 0
  4898.3     .07       0    4967     .07       0  4971.9     .07       0
  5322.3    .035       0  5436.2     .07       0
Bank Sta=4967,4971.9
XS Rating Curve= 0 ,0
Exp/Cntr=0.3,0.1

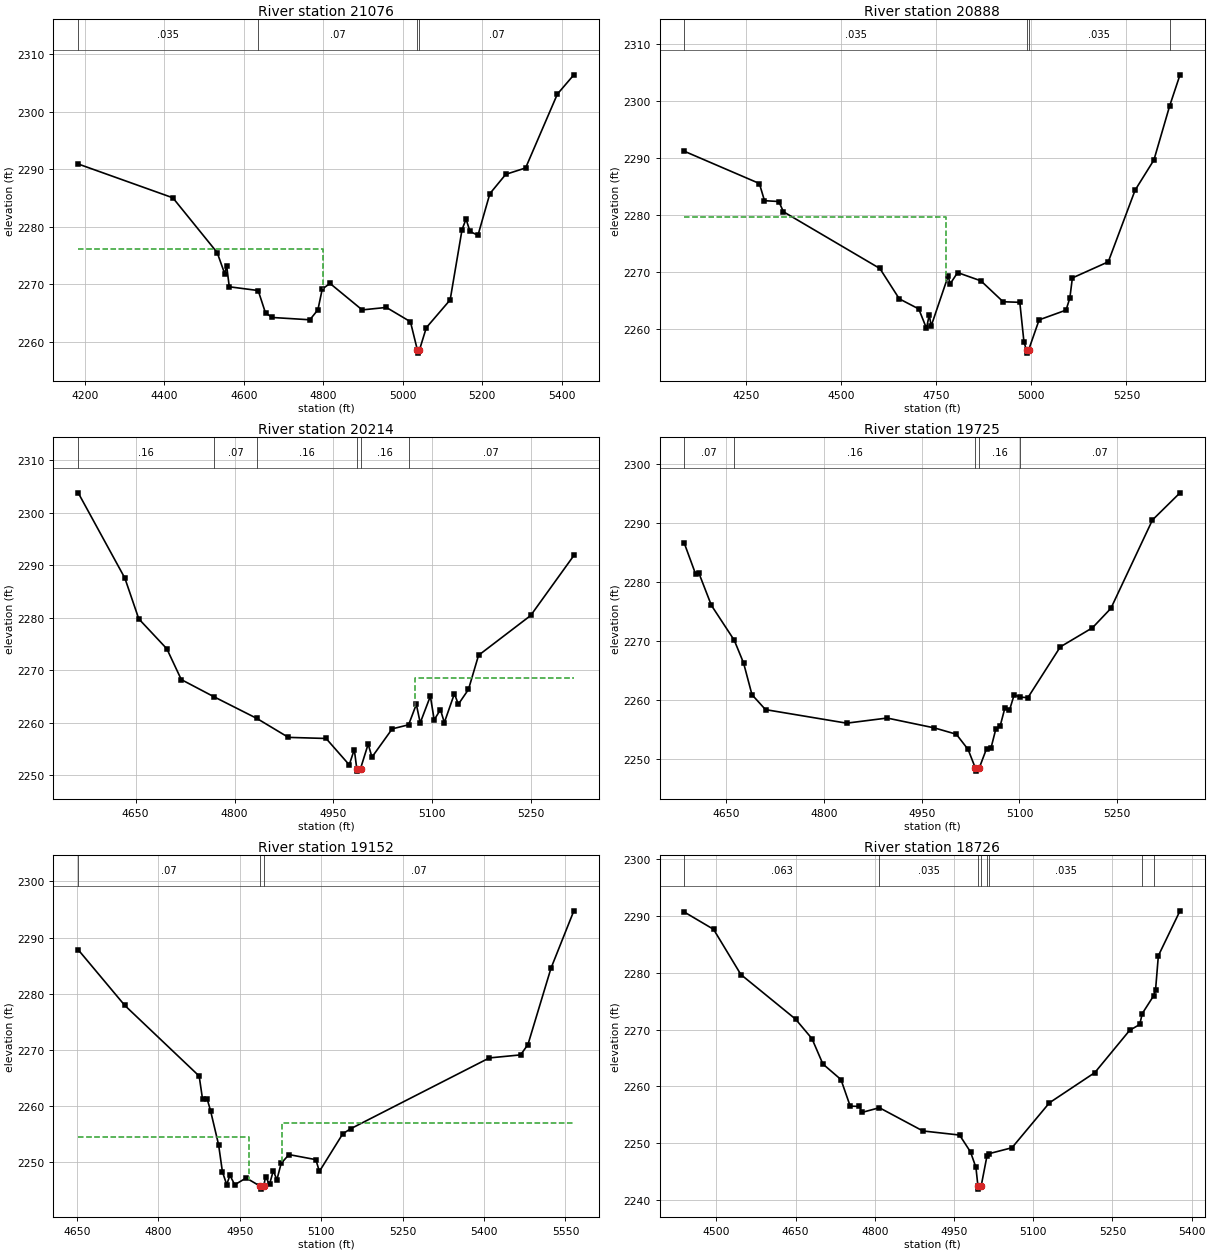
Type RM Length L Ch R = 1 ,21076   ,188,188,188
BEGIN DESCRIPTION:
Idlewild Creek 38.0
END DESCRIPTION:
XS GIS Cut Line= 3
      1362737.32      6849872.95      1362874.84       6849067.4
      1362879.41      6848636.52
#Sta/Elev= 30
  4182.8  2290.9  4421.1 2285.02  4532.7  2275.5  4551.6 2271.84  4556.7 2273.14
  4563.2 2269.54    4636 2268.89  4654.5 2264.97  4671.9  2264.2  4766.1  2263.8
  4786.4 2265.54  4797.3 2269.13  4816.8 2270.13  4897.9 2265.52  4958.8 2265.95
  5019.4 2263.46    5037  2258.5  5037.3    2258  5041.9  2258.5  5059.4 2262.43
  5119.4 2267.26  5149.4  2279.5  5159.4 2281.31  5169.4 2279.17  5189.4 2278.49
  5219.4 2285.74  5259.4  2289.1  5309.4 2290.21  5389.4 2303.06  5430.9 2306.41
#Mann= 4 ,-1 , 0
  4182.8    .035       0    4636     .07       0    5037     .07       0
  5041.9     .07       0
#XS Ineff= 2 , 0
         4799.19 2276.05
Permanent Ineff=
       F       F
Bank Sta=5037,5041.9
XS Rating Curve= 0 ,0
Exp/Cntr=0.3,0.1

Type RM Length L Ch R = 1 ,20888   ,674,674,674
BEGIN DESCRIPTION:
Idlewild Creek 37.0
END DESCRIPTION:
XS GIS Cut Line= 3
      1362836.99      6850000.96      1363024.83      6849108.41
      1363078.94      6848721.18
#Sta/Elev= 30
  4087.9 2291.15  4285.1 2285.49  4298.6 2282.47  4336.2 2282.33  4348.4 2280.53
  4601.9 2270.57    4653 2265.24  4704.1 2263.47  4724.5 2260.06  4731.7 2262.44
  4736.8 2260.47  4781.5 2269.25  4786.6 2267.86  4806.3 2269.85  4867.6  2268.4
  4925.9 2264.73  4969.8 2264.63  4980.8 2257.62  4987.7 2256.21  4988.1 2255.71
  4992.7 2256.21  5020.6 2261.55  5091.3 2263.26  5101.4 2265.39    5108 2268.91
  5202.4 2271.74    5273 2284.33  5322.4 2289.62  5363.9 2299.14    5391 2304.57
#Mann= 4 ,-1 , 0
  4087.9    .035       0  4987.7    .035       0  4992.7    .035       0
  5363.9    .063       0
#XS Ineff= 2 , 0
         4776.04 2279.63
Permanent Ineff=
       F       F
Bank Sta=4987.7,4992.7
XS Rating Curve= 0 ,0
Exp/Cntr=0.3,0.1

Type RM Length L Ch R = 1 ,20214   ,489,489,489
BEGIN DESCRIPTION:
Idlewild Creek 36.0
END DESCRIPTION:
XS GIS Cut Line= 3
      1363754.97      6849287.96      1363471.48      6848955.13
      1363304.98      6848687.97
#Sta/Elev= 30
  4562.8 2303.84  4633.6 2287.59  4654.7 2279.83  4697.3 2274.12  4719.2 2268.26
  4769.2 2264.96    4834 2260.85  4881.7 2257.25  4938.9 2257.04    4974 2252.02
  4981.7 2254.93  4985.4 2251.32  4985.9 2250.82  4991.2 2251.32  5002.7 2255.96
  5008.5 2253.49  5039.2 2258.87  5064.1 2259.65  5075.8 2263.55  5081.7 2260.01
  5097.1  2265.1  5102.9 2260.59  5112.4 2262.53  5118.3 2260.07  5133.6 2265.58
  5139.5 2263.55  5154.9 2266.38  5170.2 2272.89  5249.3 2280.47  5314.8  2291.9
#Mann= 6 ,-1 , 0
  4562.8     .16       0  4769.2     .07       0    4834     .16       0
  4985.4     .07       0  4991.2     .16       0  5064.1     .07       0
#XS Ineff= 2 , 0
                         5074.11         2268.64
Permanent Ineff=
       F       F
Bank Sta=4985.4,4991.2
XS Rating Curve= 0 ,0
Exp/Cntr=0.3,0.1

Type RM Length L Ch R = 1 ,19725   ,573,573,573
BEGIN DESCRIPTION:
Idlewild Creek 35.0
END DESCRIPTION:
XS GIS Cut Line= 3
      1363905.01      6849138.02      1363794.24       6848738.7
      1363555.02      6848488.02
#Sta/Elev= 30
  4585.6 2286.58  4602.8 2281.39  4607.9 2281.53  4627.1 2276.05  4662.2 2270.12
  4676.5 2266.26  4689.4 2260.87  4710.2 2258.33  4834.7 2256.03  4896.9  2256.9
  4969.6 2255.22  5003.1 2254.15  5021.2 2251.56  5032.4 2248.38  5032.9 2247.88
  5038.2 2248.38  5049.5 2251.69  5056.4 2251.83  5063.6 2254.97  5070.5 2255.59
  5077.8 2258.67  5084.7 2258.22  5091.9 2260.85  5101.3 2260.45    5113 2260.37
  5162.7 2268.99  5212.1 2272.24  5240.4 2275.54  5304.2 2290.56  5346.5 2295.17
#Mann= 5 ,-1 , 0
  4585.6     .07       0  4662.2     .16       0  5032.4     .07       0
  5038.2     .16       0  5101.3     .07       0
Bank Sta=5032.4,5038.2
XS Rating Curve= 0 ,0
Exp/Cntr=0.3,0.1

Type RM Length L Ch R = 1 ,19152   ,426,426,426
BEGIN DESCRIPTION:
Idlewild Creek 34.0
END DESCRIPTION:
XS GIS Cut Line= 3
      1364443.24      6848929.83      1364157.73      6848731.92
      1363719.45      6848374.57
#Sta/Elev= 30
  4652.6 2287.83  4738.3 2277.93  4875.4 2265.34  4881.6 2261.24  4890.3  2261.2
  4896.3 2259.19  4911.2  2253.1  4918.2 2248.31  4926.1 2246.02  4932.1 2247.68
  4940.9 2245.98  4961.9  2247.2  4988.2 2245.71  4988.7 2245.21  4994.2 2245.71
  4997.7 2247.42    5005 2246.06    5012 2248.51  5018.5 2246.86  5026.4  2249.8
  5040.8 2251.36  5090.3 2250.46  5096.8 2248.36  5139.9 2255.06  5154.2 2255.95
  5409.8 2268.57  5467.3 2269.11  5480.9 2270.94  5523.3 2284.52  5565.5 2294.76
#Mann= 3 ,-1 , 0
  4652.6     .07       0  4988.2     .07       0  4994.2     .07       0
#XS Ineff= 2 , 0
         4967.97 2254.55 5028.12         2256.98
Permanent Ineff=
       F       F
Bank Sta=4988.2,4994.2
XS Rating Curve= 0 ,0
Exp/Cntr=0.3,0.1

Type RM Length L Ch R = 1 ,18726   ,382,382,382
BEGIN DESCRIPTION:
Idlewild Creek 33.0
END DESCRIPTION:
XS GIS Cut Line= 3
      1364788.39      6848539.02       1364246.9      6848394.29
      1363894.72      6848256.98
#Sta/Elev= 30
  4439.5 2290.64  4494.8 2287.61  4546.5 2279.67    4650 2271.84  4681.1 2268.41
  4701.8 2263.95    4736 2261.22  4753.5 2256.55  4770.9  2256.5    4776 2255.45
  4808.8 2256.27  4891.1 2252.19  4960.6 2251.47  4981.3 2248.51  4991.6 2245.77
  4995.4 2242.47  4995.9 2241.97  5001.4 2242.47  5012.6 2247.85  5017.2 2248.22
  5059.8 2249.24  5130.8 2257.14  5216.7 2262.44  5282.7 2269.87  5301.8  2270.9
  5306.4  2272.8  5327.8  2275.9  5331.6 2276.87    5337 2282.97    5378 2290.86
#Mann= 8 ,-1 , 0
  4439.5    .063       0  4808.8    .035       0  4995.4    .035       0
  5001.4    .035       0  5012.6     .07       0  5017.2    .035       0
  5306.4     .07       0  5327.8    .035       0
Bank Sta=4995.4,5001.4
XS Rating Curve= 0 ,0
Exp/Cntr=0.3,0.1

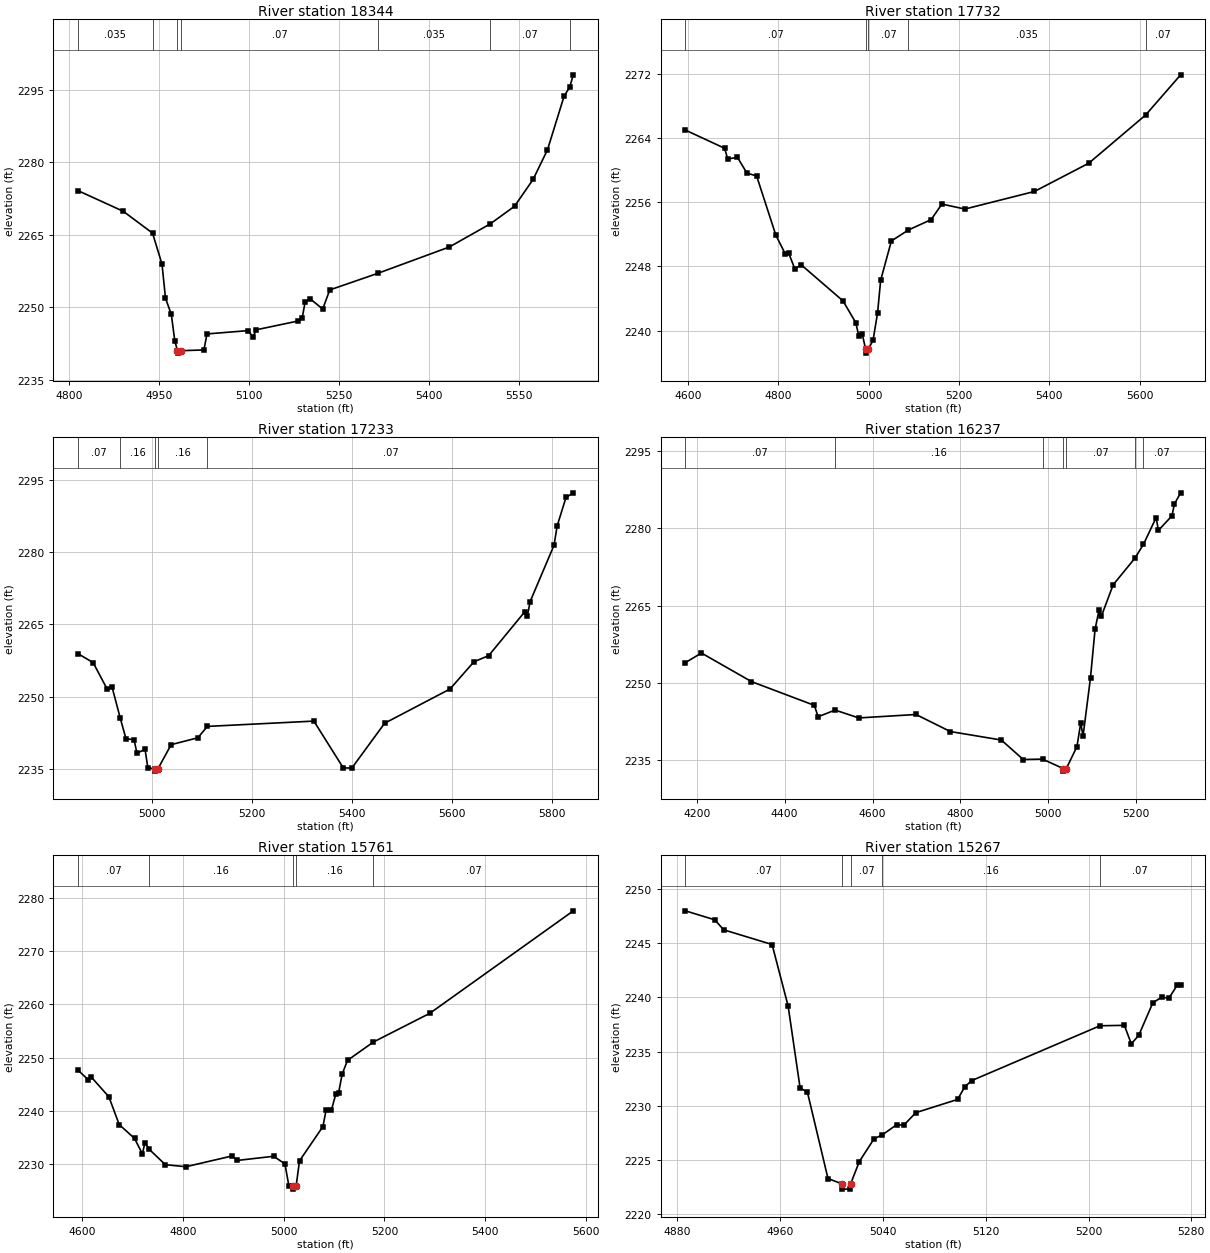
Type RM Length L Ch R = 1 ,18344   ,612,612,612
BEGIN DESCRIPTION:
Idlewild Creek 32.0
END DESCRIPTION:
XS GIS Cut Line= 3
      1364719.27      6848375.82      1364561.08      6848279.91
      1363939.95      6848121.94
#Sta/Elev= 30
    4815 2274.08  4890.2 2269.83  4939.2  2265.3    4955 2258.88  4960.8 2251.83
  4970.5  2248.5  4976.3 2243.05  4980.7 2240.98  4981.2 2240.48  4986.7 2240.98
  5024.9 2241.14    5030 2244.45  5099.1 2245.14  5106.7 2243.74  5111.9  2245.3
  5181.7 2247.12  5188.6 2247.66  5193.7 2251.08  5202.3 2251.68    5223  2249.6
  5234.7 2253.55    5315 2256.99  5434.1 2262.43  5502.2  2267.2  5542.8 2270.85
  5573.8 2276.41  5597.8 2282.54  5625.4 2293.59  5634.8 2295.51  5640.9 2298.04
#Mann= 7 ,-1 , 0
    4815    .035       0  4939.2     .07       0  4980.7     .07       0
  4986.7     .07       0    5315    .035       0  5502.2     .07       0
  5634.8    .035       0
Bank Sta=4980.7,4986.7
XS Rating Curve= 0 ,0
Exp/Cntr=0.3,0.1

Type RM Length L Ch R = 1 ,17732   ,499,499,499
BEGIN DESCRIPTION:
Idlewild Creek 31.0
END DESCRIPTION:
XS GIS Cut Line= 3
      1364979.73        6848086.      1364704.81      6847787.92
      1364024.97      6847911.61
#Sta/Elev= 30
  4594.5 2265.01  4681.4 2262.74  4688.2 2261.41  4709.8  2261.6  4730.7 2259.65
  4752.3 2259.28  4794.8  2251.9  4815.8 2249.55    4823  2249.7  4836.8  2247.7
    4851  2248.2  4943.4 2243.71  4971.7    2241  4978.5 2239.33  4985.9 2239.63
  4993.5 2237.69    4994 2237.19  4999.6 2237.69    5010 2238.79  5020.1 2242.24
  5026.8 2246.27  5050.6 2251.18  5088.4 2252.55  5138.6 2253.84  5162.4 2255.78
  5213.3 2255.16  5367.2 2257.35  5487.7 2260.88  5613.5 2266.89    5691  2271.9
#Mann= 5 ,-1 , 0
  4594.5     .07       0  4993.5     .07       0  4999.6     .07       0
  5088.4    .035       0  5613.5     .07       0
Bank Sta=4993.5,4999.6
XS Rating Curve= 0 ,0
Exp/Cntr=0.3,0.1

Type RM Length L Ch R = 1 ,17233   ,996,996,996
BEGIN DESCRIPTION:
Idlewild Creek 30.0
END DESCRIPTION:
XS GIS Cut Line= 3
      1365055.01      6847638.01      1364985.23      6847507.83
      1364205.04      6847188.01
#Sta/Elev= 30
  4852.3 2258.91  4882.4 2257.07    4910 2251.68  4920.4 2251.97  4936.9 2245.49
  4948.2 2241.28  4964.4 2241.09  4970.1 2238.27  4986.3 2239.11    4992 2235.23
  5006.1 2235.07  5006.6 2234.57  5012.2 2235.07  5038.6 2240.06    5092 2241.48
  5110.9 2243.84  5324.1 2244.94  5382.9 2235.24  5400.1 2235.21  5465.7  2244.5
  5596.4 2251.59  5644.4 2257.24  5673.8 2258.51  5745.8 2267.57  5751.2 2266.75
  5756.8 2269.73  5804.6 2281.41  5810.8 2285.39  5828.5  2291.3  5843.2 2292.26
#Mann= 5 ,-1 , 0
  4852.3     .07       0  4936.9     .16       0  5006.1     .07       0
  5012.2     .16       0  5110.9     .07       0
Bank Sta=5006.1,5012.2
XS Rating Curve= 0 ,0
Exp/Cntr=0.3,0.1

Type RM Length L Ch R = 1 ,16237   ,476,476,476
BEGIN DESCRIPTION:
Idlewild Creek 29.0
END DESCRIPTION:
XS GIS Cut Line= 3
      1365204.99      6847337.99      1364528.24      6846864.59
      1364235.79      6846936.26
#Sta/Elev= 30
  4174.1  2253.9  4210.7 2255.77  4324.5 2250.21  4467.5 2245.59  4476.2 2243.37
  4514.8 2244.67  4568.7 2243.14  4698.9 2243.81  4777.1 2240.49  4893.1 2238.84
  4942.9 2235.05  4986.8 2235.13  5033.9 2233.29  5034.4 2232.79  5040.9 2233.29
  5065.1 2237.55  5073.8 2242.19    5079  2239.6    5096    2251  5106.3 2260.36
  5115.4 2264.13  5120.5 2262.89  5147.5 2269.04  5196.9 2274.21  5216.5 2276.92
  5245.3 2282.12  5250.5 2279.64  5281.3 2282.46  5286.9 2284.77  5301.1 2286.94
#Mann= 7 ,-1 , 0
  4174.1     .07       0  4514.8     .16       0  4986.8     .07       0
  5033.9     .07       0  5040.9     .07       0  5196.9    .035       0
  5216.5     .07       0
Bank Sta=5033.9,5040.9
XS Rating Curve= 0 ,0
Exp/Cntr=0.3,0.1

Type RM Length L Ch R = 1 ,15761   ,494,494,494
BEGIN DESCRIPTION:
Idlewild Creek 28.0
END DESCRIPTION:
XS GIS Cut Line= 3
      1365054.99      6847187.97      1364975.26      6846787.54
      1364785.99      6846244.68
#Sta/Elev= 30
  4591.7 2247.63  4612.1 2245.83  4617.2 2246.43  4652.9 2242.64  4673.4 2237.42
  4703.8 2234.83  4719.4 2231.92  4724.5 2234.02  4732.5 2232.82    4765 2229.89
  4805.8 2229.51  4897.6 2231.53  4907.8 2230.69    4980 2231.47  5002.4 2230.04
  5010.1 2225.95  5017.4  2225.8  5017.9  2225.3  5024.5  2225.8  5031.3 2230.61
  5077.8 2237.06  5084.2 2240.21  5094.8 2240.22  5103.6 2243.22  5108.9 2243.39
    5116 2246.91  5126.6 2249.49  5178.1 2252.94    5290 2258.33  5574.9 2277.58
#Mann= 5 ,-1 , 0
  4591.7     .07       0  4732.5     .16       0  5017.4     .07       0
  5024.5     .16       0  5178.1     .07       0
Bank Sta=5017.4,5024.5
XS Rating Curve= 0 ,0
Exp/Cntr=0.3,0.1

Type RM Length L Ch R = 1 ,15267   ,474,474,474
BEGIN DESCRIPTION:
Idlewild Creek 27.0
END DESCRIPTION:
XS GIS Cut Line= 3
        1365205.        6847138.       1365260.2      6847038.48
      1365154.99      6846787.97
#Sta/Elev= 30
  4886.2 2247.99  4909.1 2247.16    4916 2246.24  4953.7 2244.88  4966.2 2239.19
  4975.5 2231.64  4981.2 2231.25  4997.2 2223.28  5007.8  2222.8  5008.3  2222.3
  5014.4  2222.3  5014.9  2222.8  5021.6 2224.85  5033.1 2226.95  5039.5 2227.31
  5050.7 2228.25  5056.2  2228.2  5065.6 2229.36  5098.1 2230.58  5103.7 2231.75
  5109.1 2232.32  5208.9 2237.38  5227.9 2237.42  5233.3 2235.71  5239.1  2236.5
    5250 2239.49  5257.1 2240.04  5262.5 2239.91    5269 2241.12  5271.7 2241.12
#Mann= 5 ,-1 , 0
  4886.2     .07       0  5007.8     .07       0  5014.9     .07       0
  5039.5     .16       0  5208.9     .07       0
Bank Sta=5007.8,5014.9
XS Rating Curve= 0 ,0
Exp/Cntr=0.3,0.1

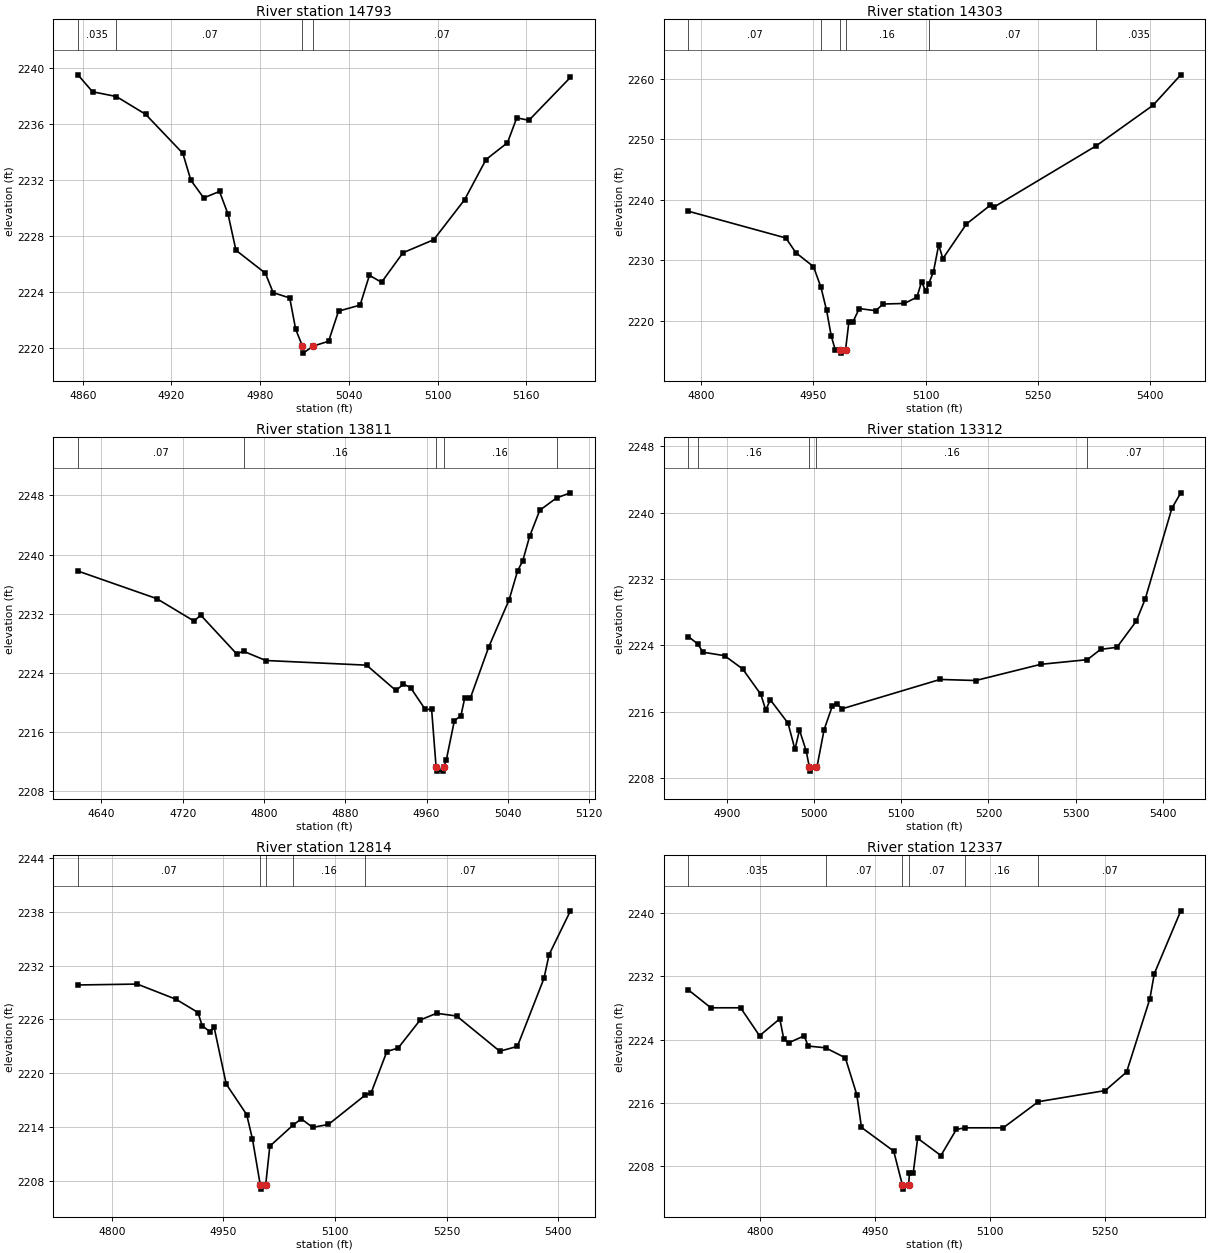
Type RM Length L Ch R = 1 ,14793   ,490,490,490
BEGIN DESCRIPTION:
Idlewild Creek 26.0
END DESCRIPTION:
XS GIS Cut Line= 3
      1365654.99      6846887.98      1365605.87      6846753.36
      1365455.02      6846638.01
#Sta/Elev= 30
  4856.7 2239.53  4866.6 2238.32  4882.7 2237.98  4902.5 2236.71  4927.7 2233.92
  4933.1    2232  4941.8 2230.74  4952.5  2231.2  4958.3 2229.56  4963.6    2227
  4983.5 2225.36  4988.8 2223.97    5000 2223.59    5004 2221.36  5008.6 2220.15
  5009.1 2219.65  5015.8 2220.15  5026.3  2220.5    5033 2222.65  5047.6 2223.08
  5053.9 2225.21  5062.1 2224.71  5076.6 2226.82  5097.4 2227.75  5118.3 2230.61
  5132.8 2233.48  5147.3 2234.68  5153.6 2236.46  5161.8 2236.28  5189.9 2239.35
#Mann= 4 ,-1 , 0
  4856.7    .035       0  4882.7     .07       0  5008.6     .07       0
  5015.8     .07       0
Bank Sta=5008.6,5015.8
XS Rating Curve= 0 ,0
Exp/Cntr=0.3,0.1

Type RM Length L Ch R = 1 ,14303   ,492,492,492
BEGIN DESCRIPTION:
Idlewild Creek 25.0
END DESCRIPTION:
XS GIS Cut Line= 3
      1365904.98      6846888.04      1365989.94      6846688.14
      1365805.01      6846288.01
#Sta/Elev= 30
  4782.8 2238.11  4913.2 2233.68  4926.5 2231.25  4950.1 2228.94  4960.1 2225.51
  4967.6 2221.71  4973.8 2217.47  4979.2 2215.16  4985.7 2215.13  4986.2 2214.63
  4992.9 2215.13  4997.4 2219.81  5002.8 2219.81  5011.2    2222  5033.2 2221.65
  5043.1 2222.75  5071.6 2222.85  5088.3 2223.89  5094.5 2226.45    5100 2224.86
    5104  2226.1  5110.3 2228.06  5117.4 2232.55  5122.9 2230.26  5154.4 2235.99
  5186.2 2239.09  5191.7 2238.83  5328.1 2248.95  5403.7 2255.63  5440.8 2260.67
#Mann= 6 ,-1 , 0
  4782.8     .07       0  4960.1     .16       0  4985.7     .07       0
  4992.9     .16       0    5104     .07       0  5328.1    .035       0
Bank Sta=4985.7,4992.9
XS Rating Curve= 0 ,0
Exp/Cntr=0.3,0.1

Type RM Length L Ch R = 1 ,13811   ,499,499,499
BEGIN DESCRIPTION:
Idlewild Creek 24.0
END DESCRIPTION:
XS GIS Cut Line= 3
        1366205.        6847088.      1366444.57      6846789.05
        1366455.      6846687.99
#Sta/Elev= 30
  4616.9 2237.79  4694.5 2234.06  4731.3 2231.02  4737.7 2231.84    4773 2226.61
    4780 2226.94  4801.8  2225.7    4901 2225.07  4929.8 2221.65  4937.3  2222.5
  4944.2 2222.05  4958.6 2219.11    4965 2219.08  4969.4 2211.25  4969.9 2210.75
  4976.2 2210.75  4976.7 2211.25  4979.4 2212.24  4987.4 2217.58  4993.8 2218.23
  4997.5 2220.58    5003 2220.58  5021.2 2227.53  5041.3 2233.92  5049.6 2237.82
  5054.6 2239.14  5061.4 2242.46  5071.4    2246    5088 2247.68  5101.6 2248.36
#Mann= 5 ,-1 , 0
  4616.9     .07       0    4780     .16       0  4969.4     .07       0
  4976.7     .16       0    5088     .07       0
Bank Sta=4969.4,4976.7
XS Rating Curve= 0 ,0
Exp/Cntr=0.3,0.1

Type RM Length L Ch R = 1 ,13312   ,498,498,498
BEGIN DESCRIPTION:
Idlewild Creek 23.0
END DESCRIPTION:
XS GIS Cut Line= 3
        1366805.      6847038.01      1366845.45      6846899.08
        1366755.      6846488.02
#Sta/Elev= 30
  4855.3 2225.06  4866.1 2224.19  4872.1 2223.18    4897 2222.76  4917.8 2221.16
  4938.6  2218.1  4944.3 2216.21  4949.5 2217.45  4969.9 2214.63  4977.8 2211.47
    4983 2213.81  4990.7  2211.3  4994.3 2209.36  4994.8 2208.86  5001.6 2209.36
  5003.1 2209.36  5011.3 2213.85  5020.9 2216.75    5026 2216.99  5031.8 2216.36
  5144.5  2219.9  5185.4 2219.77  5260.1 2221.72  5313.6 2222.28  5328.8 2223.52
  5347.6 2223.77  5369.7 2226.91    5380 2229.57  5410.7 2240.52  5420.9 2242.37
#Mann= 5 ,-1 , 0
  4855.3     .07       0  4866.1     .16       0  4994.3     .07       0
  5001.6     .16       0  5313.6     .07       0
Bank Sta=4994.3,5001.6
XS Rating Curve= 0 ,0
Exp/Cntr=0.3,0.1

Type RM Length L Ch R = 1 ,12814   ,477,477,477
BEGIN DESCRIPTION:
Idlewild Creek 22.0
END DESCRIPTION:
XS GIS Cut Line= 3
      1366739.19      6847230.79      1366954.59        6847113.
      1367304.97      6846888.02
#Sta/Elev= 30
  4754.5 2229.85  4834.2 2229.95  4886.5 2228.25  4915.8 2226.78  4921.5  2225.3
  4931.9 2224.64  4937.6 2225.11  4953.8  2218.8  4981.3 2215.39  4989.1 2212.65
  4999.5 2207.58    5000 2207.08  5006.9 2207.58  5012.4 2211.87  5043.2 2214.19
  5054.7 2214.92  5069.9 2213.97  5091.1 2214.29  5140.5 2217.56  5148.6 2217.83
  5169.7 2222.43  5184.9 2222.82  5214.4 2225.94  5236.4 2226.69  5263.5 2226.39
  5321.4 2222.46  5345.1    2223  5380.8 2230.58  5387.7 2233.23  5416.4 2238.12
#Mann= 5 ,-1 , 0
  4754.5     .07       0  4999.5     .07       0  5006.9     .07       0
  5043.2     .16       0  5140.5     .07       0
Bank Sta=4999.5,5006.9
XS Rating Curve= 0 ,0
Exp/Cntr=0.3,0.1

Type RM Length L Ch R = 1 ,12337   ,594,594,594
BEGIN DESCRIPTION:
Idlewild Creek 21.0
END DESCRIPTION:
XS GIS Cut Line= 3
      1367211.39      6847512.95      1367303.28      6847233.78
        1367355.      6846888.03
#Sta/Elev= 30
  4706.1 2230.28  4735.6 2228.01  4774.5 2228.01  4799.2 2224.48  4825.7 2226.62
    4831 2224.01  4837.6  2223.6  4857.5 2224.47  4862.8 2223.18  4885.4 2222.96
  4911.3  2221.7  4926.3 2217.04  4932.4 2212.91  4974.5 2209.92  4985.9 2205.62
  4986.4 2205.12    4994 2205.62  4995.1 2207.15    5000 2207.15  5005.8 2211.54
  5036.2 2209.36  5056.4 2212.66  5067.5 2212.86  5117.6 2212.86  5163.5 2216.16
  5250.9 2217.56  5278.8  2219.9  5309.2 2229.14    5315 2232.32  5349.6 2240.25
#Mann= 6 ,-1 , 0
  4706.1    .035       0  4885.4     .07       0  4985.9     .07       0
    4994     .07       0  5067.5     .16       0  5163.5     .07       0
Bank Sta=4985.9,4994
XS Rating Curve= 0 ,0
Exp/Cntr=0.3,0.1