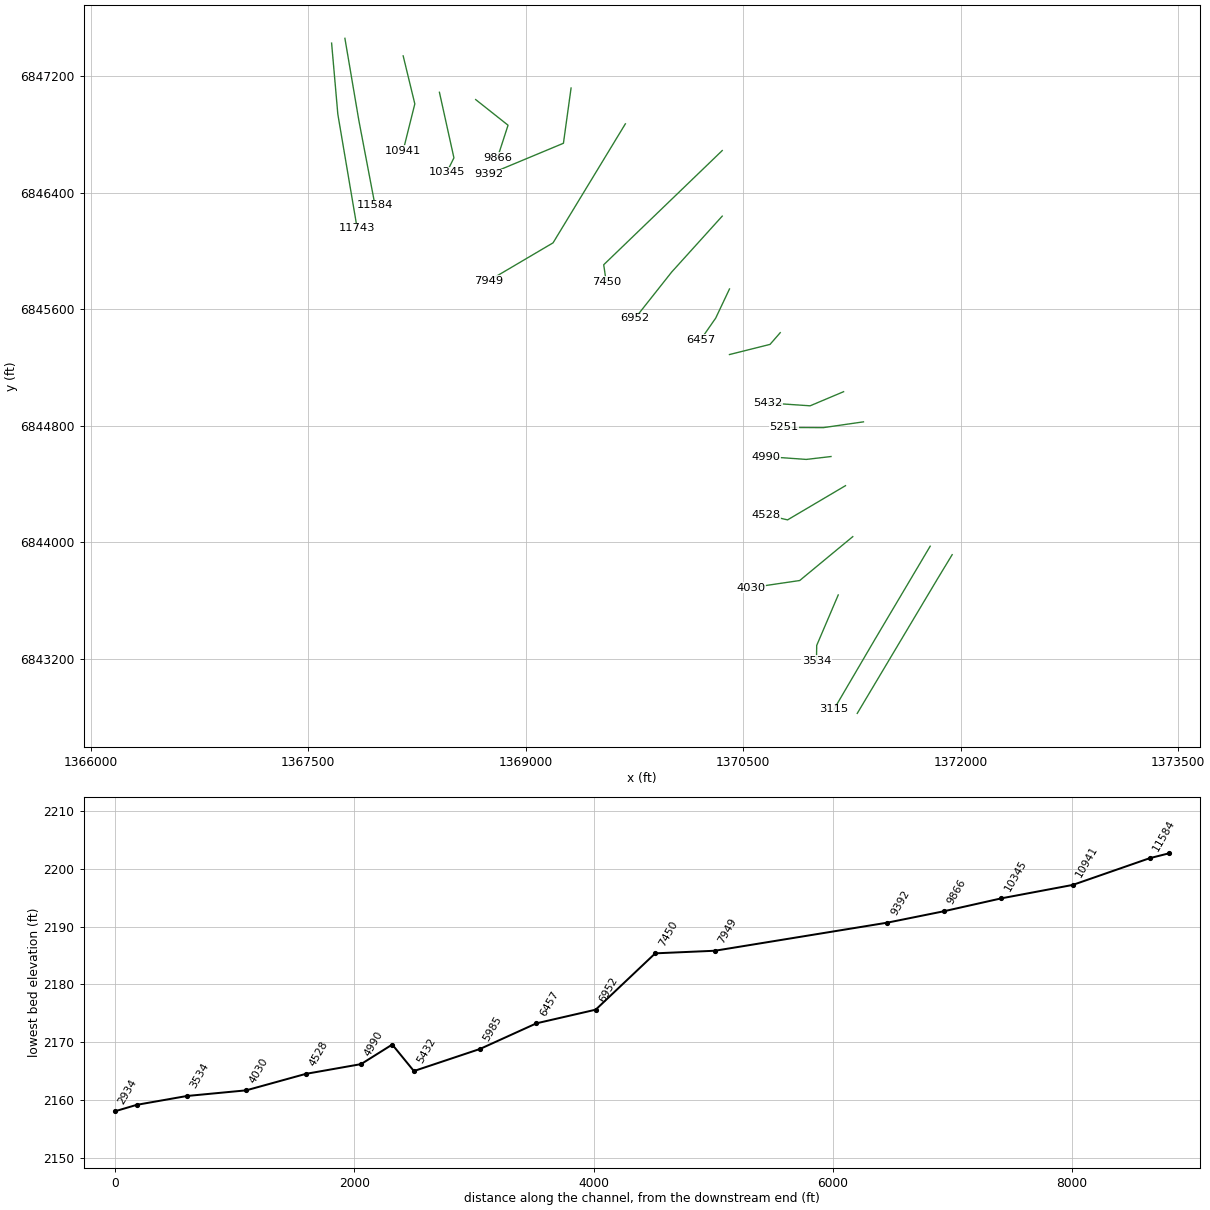
HEC-RAS study Idlewild Creek.prj: Idlewild Creek Base Level Engineering

--- Idlewild Creek.g01 (geometry) --- (continued)

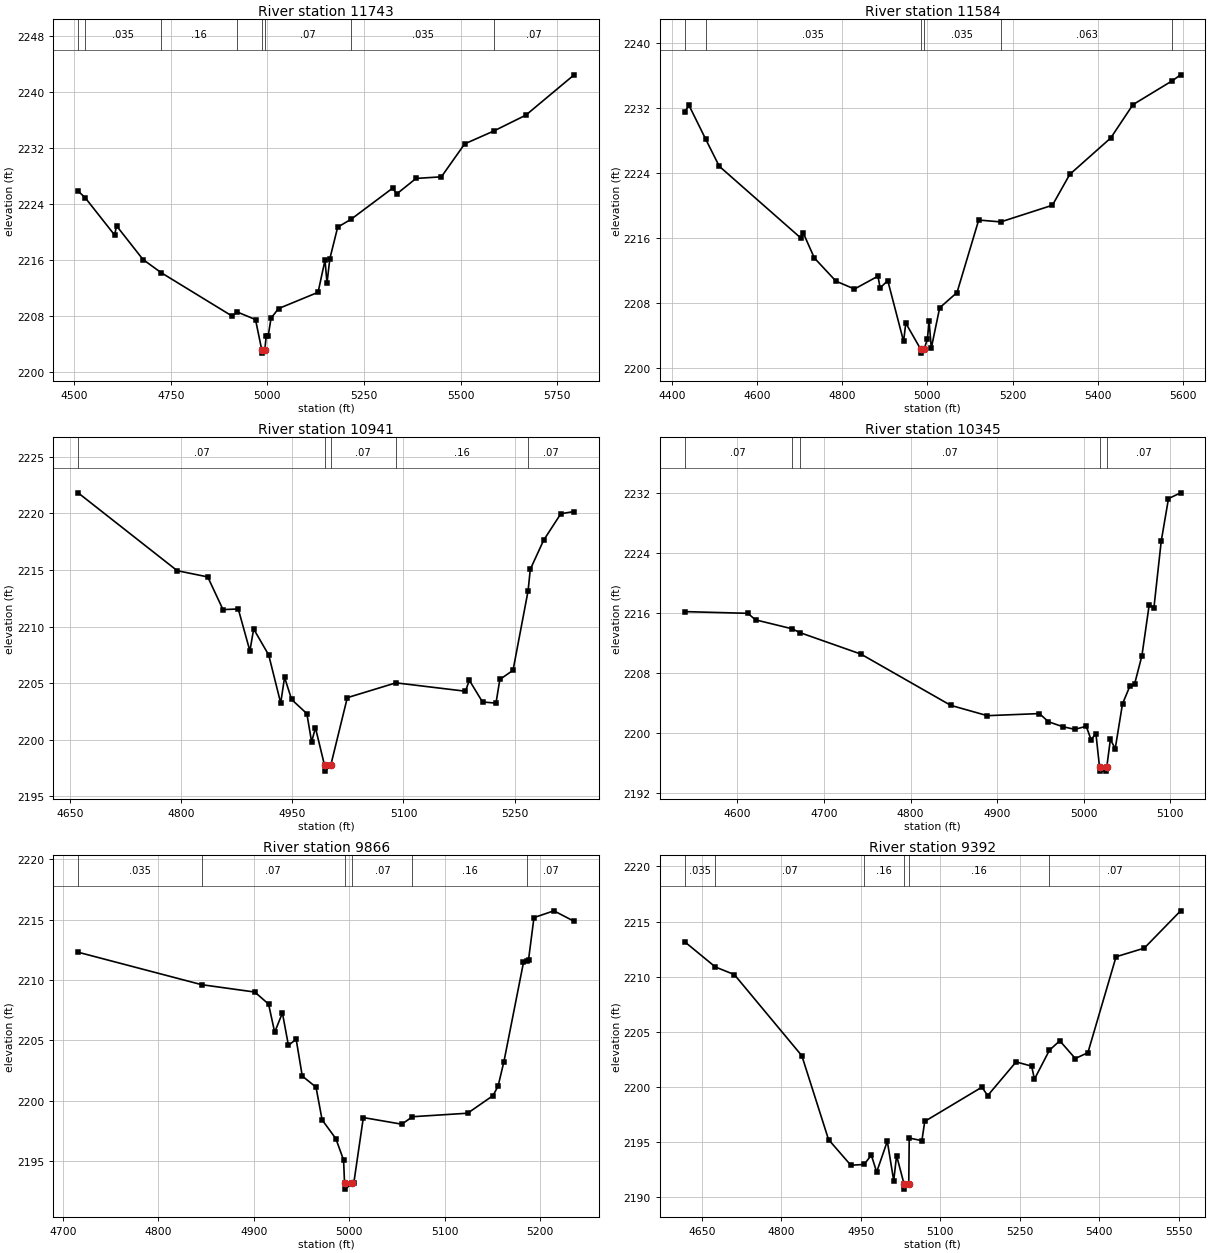
Type RM Length L Ch R = 1 ,11743   ,159,159,159
BEGIN DESCRIPTION:
Idlewild Creek 20.0
END DESCRIPTION:
XS GIS Cut Line= 3
      1367661.58       6847425.4      1367704.49      6846937.49
      1367837.73      6846154.64
#Sta/Elev= 30
  4510.2 2225.88  4529.1 2224.88  4604.7 2219.58  4609.7  2220.9  4678.2 2216.08
  4725.2  2214.2  4909.1 2207.98  4921.4 2208.59  4969.4 2207.49  4985.4 2203.19
  4985.9 2202.69  4993.5 2203.19  4997.2 2205.18  5002.3 2205.18  5009.6 2207.69
  5028.9 2209.06  5131.3 2211.39  5149.3 2215.99  5154.4 2212.71  5161.8  2216.2
  5182.1 2220.71  5217.3 2221.86  5324.1 2226.28  5335.1 2225.47  5384.9 2227.68
  5450.5 2227.91  5510.7 2232.62  5585.6 2234.45    5669 2236.73  5794.1  2242.5
#Mann= 8 ,-1 , 0
  4510.2    .063       0  4529.1    .035       0  4725.2     .16       0
  4921.4     .07       0  4985.4     .07       0  4993.5     .07       0
  5217.3    .035       0  5585.6     .07       0
Bank Sta=4985.4,4993.5
XS Rating Curve= 0 ,0
Exp/Cntr=0.3,0.1

Type RM Length L Ch R = 1 ,11584   ,643,643,643
BEGIN DESCRIPTION:
Idlewild Creek 19.0
END DESCRIPTION:
XS GIS Cut Line= 3
      1367753.23      6847458.33      1367849.09      6846896.45
      1367960.92      6846312.36
#Sta/Elev= 30
    4430  2231.5  4440.5 2232.31  4479.8 2228.14  4511.5 2224.83  4703.6 2215.98
  4708.7 2216.63  4734.7 2213.56  4785.4 2210.71    4829 2209.74  4884.1 2211.32
  4889.2 2209.87  4907.1 2210.78  4944.3  2203.3  4949.4 2205.55  4984.2 2202.36
  4984.7 2201.86  4992.4 2202.36    5000 2203.54  5004.2 2205.77  5009.3 2202.47
    5029 2207.43  5069.7 2209.31  5120.6 2218.22  5172.4 2217.99  5293.7 2220.04
  5334.4 2223.83  5430.7 2228.31  5482.7  2232.4  5575.1 2235.34  5594.7 2236.07
#Mann= 6 ,-1 , 0
    4430    .063       0  4479.8    .035       0  4984.2    .035       0
  4992.4    .035       0  5172.4    .063       0  5575.1    .035       0
Bank Sta=4984.2,4992.4
XS Rating Curve= 0 ,0
Exp/Cntr=0.3,0.1

Type RM Length L Ch R = 1 ,10941   ,596,596,596
BEGIN DESCRIPTION:
Idlewild Creek 18.0
END DESCRIPTION:
XS GIS Cut Line= 3
        1368155.      6847338.02      1368235.38      6847008.48
        1368155.      6846688.01
#Sta/Elev= 30
  4660.8 2221.82  4794.6 2214.94  4835.8 2214.39  4856.4  2211.5    4877 2211.56
  4892.7 2207.85  4897.8 2209.79  4918.1 2207.49  4934.3 2203.24  4939.5 2205.52
    4949 2203.56  4969.6 2202.31    4976 2199.81  4981.2 2201.06  4993.5 2197.73
    4994 2197.23  5001.8 2197.73  5024.2 2203.72  5089.8 2205.03  5183.7 2204.29
  5188.9 2205.26  5206.7 2203.34  5224.9 2203.24  5230.1 2205.33  5247.9 2206.14
  5268.2 2213.15  5271.2 2215.06  5289.2 2217.63  5312.4 2219.97  5330.4 2220.17
#Mann= 5 ,-1 , 0
  4660.8     .07       0  4993.5     .07       0  5001.8     .07       0
  5089.8     .16       0  5268.2     .07       0
Bank Sta=4993.5,5001.8
XS Rating Curve= 0 ,0
Exp/Cntr=0.3,0.1

Type RM Length L Ch R = 1 ,10345   ,479,479,479
BEGIN DESCRIPTION:
Idlewild Creek 17.0
END DESCRIPTION:
XS GIS Cut Line= 3
        1368405.      6847088.01        1368505.      6846637.98
        1368455.      6846537.99
#Sta/Elev= 30
    4539 2216.17    4612 2215.94    4621 2215.07  4662.8 2213.89  4672.5 2213.36
  4742.6 2210.51  4846.3 2203.68  4888.6  2202.3  4948.8 2202.58    4959  2201.5
  4975.7 2200.83  4989.7 2200.48  5002.8 2200.89  5008.4 2199.11    5014 2199.91
  5018.2 2195.41  5018.7 2194.91    5026 2194.91  5026.5 2195.41  5030.7 2199.13
  5036.3 2197.91  5044.7 2203.88  5053.1  2206.2  5058.7 2206.54  5067.1 2210.28
  5075.5 2217.05    5081 2216.71  5089.4 2225.55  5097.8 2231.23  5111.8    2232
#Mann= 5 ,-1 , 0
    4539     .07       0  4662.8    .035       0  4672.5     .07       0
  5018.2     .07       0  5026.5     .07       0
Bank Sta=5018.2,5026.5
XS Rating Curve= 0 ,0
Exp/Cntr=0.3,0.1

Type RM Length L Ch R = 1 ,9866    ,474,474,474
BEGIN DESCRIPTION:
Idlewild Creek 16.0
END DESCRIPTION:
XS GIS Cut Line= 3
        1368655.        6847038.      1368878.13      6846861.99
      1368805.01      6846638.02
#Sta/Elev= 30
  4715.8 2212.31  4845.3 2209.62    4901 2209.01  4915.4 2208.01  4921.8 2205.68
  4929.9 2207.28  4936.2 2204.59  4944.3  2205.1  4950.7 2202.05  4965.1 2201.13
  4971.5 2198.42  4985.9 2196.86    4994 2195.09    4995 2193.18  4995.5 2192.68
  5003.3 2193.18  5004.7 2193.18  5014.7 2198.61    5055 2198.06  5066.2 2198.68
    5124 2198.97  5150.6 2200.43  5155.9 2201.22    5162 2203.24  5182.5 2211.46
  5186.2 2211.61  5187.8 2211.68  5193.5 2215.18  5214.4 2215.74  5235.6 2214.87
#Mann= 6 ,-1 , 0
  4715.8    .035       0  4845.3     .07       0    4995     .07       0
  5003.3     .07       0  5066.2     .16       0  5186.2     .07       0
Bank Sta=4995,5003.3
XS Rating Curve= 0 ,0
Exp/Cntr=0.3,0.1

Type RM Length L Ch R = 1 ,9392    ,1443,1443,1443
BEGIN DESCRIPTION:
Idlewild Creek 15.0
END DESCRIPTION:
XS GIS Cut Line= 3
      1369312.78      6847117.35      1369260.04       6846738.1
      1368748.41      6846525.87
#Sta/Elev= 30
  4617.1 2213.17  4675.3 2210.87  4711.1 2210.18  4838.6 2202.81    4889  2195.2
  4931.1 2192.87  4956.2 2192.94  4969.8 2193.79  4979.9 2192.25    5000 2195.05
  5012.1 2191.46  5017.5 2193.75  5031.4  2191.2  5031.9  2190.7  5040.5  2191.2
  5041.4 2195.34  5065.3  2195.1  5070.7 2196.85  5178.7 2199.96  5189.5 2199.19
  5243.2 2202.25  5272.5 2201.87  5277.9 2200.69  5306.1 2203.31  5325.7 2204.17
    5355 2202.56  5378.8 2203.09    5432  2211.8  5485.2 2212.58  5553.9 2215.97
#Mann= 6 ,-1 , 0
  4617.1    .035       0  4675.3     .07       0  4956.2     .16       0
  5031.4     .07       0  5040.5     .16       0  5306.1     .07       0
Bank Sta=5031.4,5040.5
XS Rating Curve= 0 ,0
Exp/Cntr=0.3,0.1

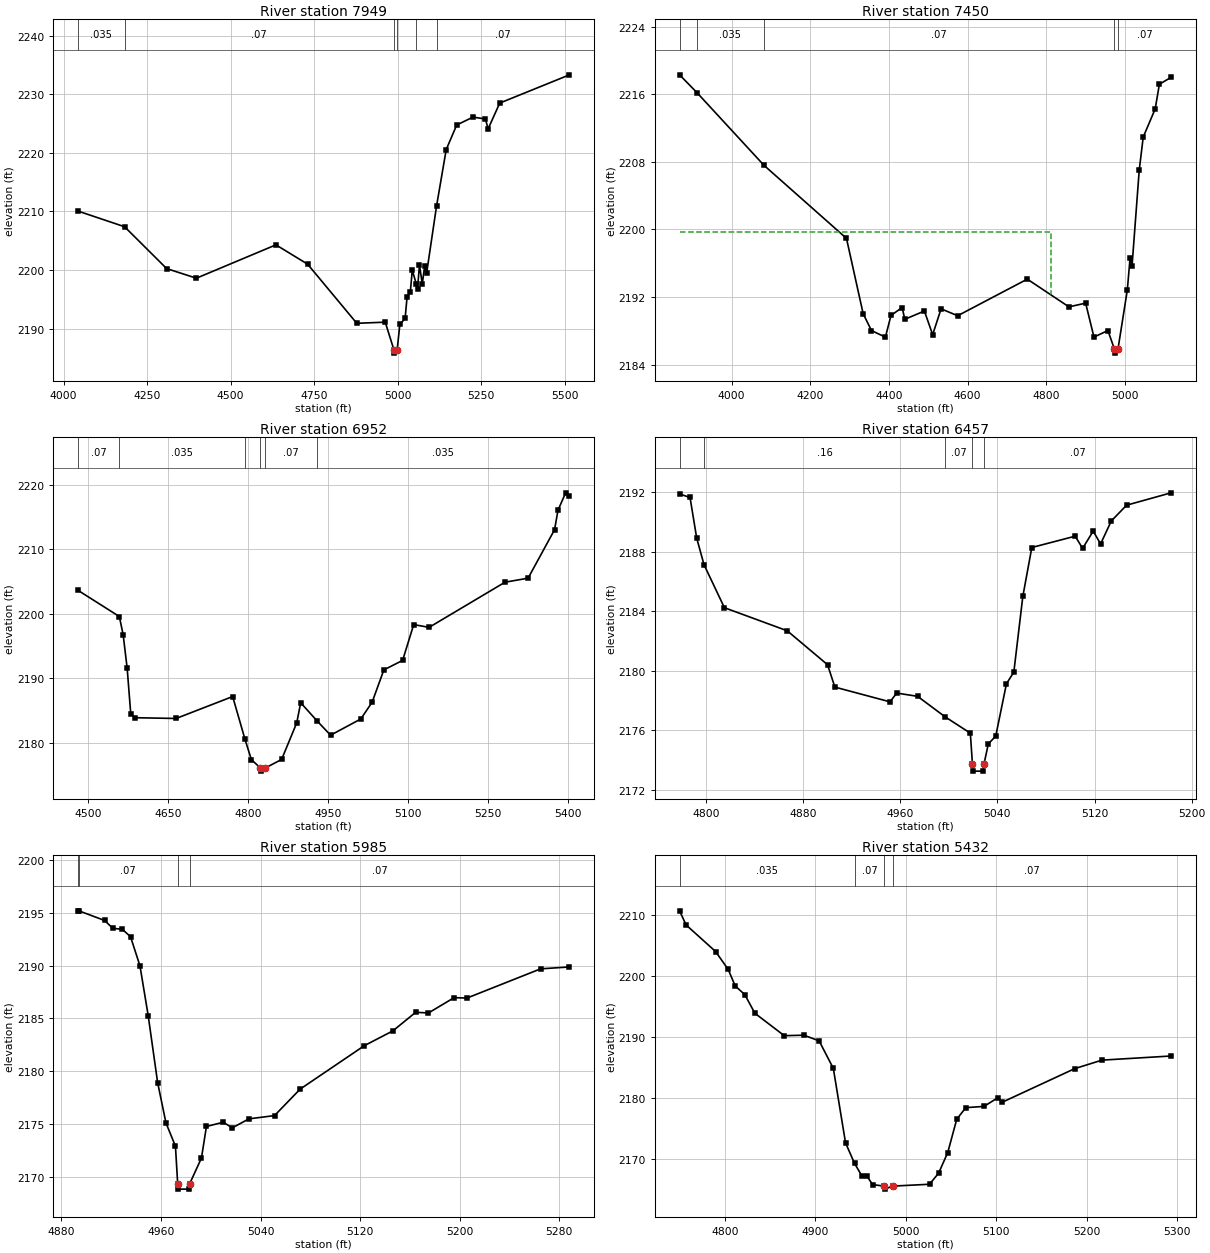
Type RM Length L Ch R = 1 ,7949    ,499,499,499
BEGIN DESCRIPTION:
Idlewild Creek 14.0
END DESCRIPTION:
XS GIS Cut Line= 3
       1369687.1      6846871.43      1369188.48      6846054.59
      1368744.93      6845794.46
#Sta/Elev= 30
    4043 2210.06  4182.4 2207.39  4308.4 2200.25  4397.4 2198.61  4635.5  2204.3
  4730.4    2201  4877.5 2190.92  4962.7 2191.11    4989 2186.33  4989.5 2185.83
  4998.2 2186.33  5006.5 2190.75  5022.2 2191.74    5028  2195.4  5037.8 2196.28
  5043.6 2199.97  5055.7 2197.62  5059.3 2196.75  5065.1 2200.83  5073.6 2197.67
  5080.8 2200.71  5086.6 2199.49  5116.2 2210.89  5145.2 2220.55  5176.6 2224.74
  5225.3 2226.09  5262.5 2225.77  5270.7 2224.09  5305.4 2228.48  5514.2  2233.3
#Mann= 6 ,-1 , 0
    4043    .035       0  4182.4     .07       0    4989     .07       0
  4998.2     .07       0  5055.7     .16       0  5116.2     .07       0
Bank Sta=4989,4998.2
XS Rating Curve= 0 ,0
Exp/Cntr=0.3,0.1

Type RM Length L Ch R = 1 ,7450    ,498,498,498
BEGIN DESCRIPTION:
Idlewild Creek 13.0
END DESCRIPTION:
XS GIS Cut Line= 3
      1370354.99      6846687.99      1369537.78      6845904.24
        1369555.      6845788.01
#Sta/Elev= 30
  3867.7 2218.29  3911.6  2216.2  4082.3 2207.59  4292.1 2198.95  4334.5 2190.05
  4355.6 2188.05  4391.1 2187.27  4405.3 2189.84  4433.6 2190.77  4440.5 2189.38
  4490.2 2190.36  4511.3 2187.56  4532.7 2190.62  4574.8  2189.8  4751.9 2194.13
  4857.8 2190.85  4900.3 2191.29  4921.4 2187.28  4956.9 2188.05  4973.3 2185.88
  4973.8 2185.38  4982.6 2185.88  5006.3 2192.86  5013.3 2196.66  5018.3 2195.73
  5036.6 2207.05  5046.7 2210.93  5077.1 2214.26  5087.8 2217.18  5117.5 2217.99
#Mann= 5 ,-1 , 0
  3867.7     .07       0  3911.6    .035       0  4082.3     .07       0
  4973.3     .07       0  4982.6     .07       0
#XS Ineff= 2 , 0
          4813.4 2199.69
Permanent Ineff=
       F       F
Bank Sta=4973.3,4982.6
XS Rating Curve= 0 ,0
Exp/Cntr=0.3,0.1

Type RM Length L Ch R = 1 ,6952    ,495,495,495
BEGIN DESCRIPTION:
Idlewild Creek 12.0
END DESCRIPTION:
XS GIS Cut Line= 3
      1370355.03      6846238.03      1370006.08      6845853.85
      1369754.99      6845537.99
#Sta/Elev= 30
    4481 2203.64  4558.6 2199.58  4565.8 2196.74  4573.3 2191.56    4580 2184.54
  4587.5  2183.9  4665.2 2183.78  4771.3 2187.18  4794.1 2180.65  4806.4  2177.4
  4823.3 2176.12  4823.8 2175.62  4832.8 2176.12  4863.2 2177.43  4891.6 2183.11
    4899 2186.22  4929.3 2183.44  4955.1 2181.19  5011.8  2183.7    5033 2186.29
  5055.1 2191.31  5090.3 2192.78  5111.1 2198.33    5140  2197.9  5282.5  2204.9
  5325.8 2205.52  5375.5 2213.04  5381.9 2216.05  5396.3 2218.75  5403.5  2218.3
#Mann= 6 ,-1 , 0
    4481     .07       0  4558.6    .035       0  4794.1     .07       0
  4823.3    .035       0  4832.8     .07       0  4929.3    .035       0
Bank Sta=4823.3,4832.8
XS Rating Curve= 0 ,0
Exp/Cntr=0.3,0.1

Type RM Length L Ch R = 1 ,6457    ,472,472,472
BEGIN DESCRIPTION:
Idlewild Creek 11.0
END DESCRIPTION:
XS GIS Cut Line= 3
      1370405.01      6845738.01      1370309.97      6845537.94
      1370205.02      6845388.02
#Sta/Elev= 30
  4778.5 2191.86  4787.1 2191.63  4792.6  2188.9  4798.6 2187.12  4815.4 2184.23
  4867.1 2182.68  4900.3  2180.4  4906.3  2178.9  4951.7 2177.91  4957.2  2178.5
  4974.4 2178.28  4997.1  2176.9  5017.8 2175.81  5019.5 2173.76    5020 2173.26
  5028.6 2173.26  5029.1 2173.76  5032.6 2175.09  5038.7 2175.61  5047.5 2179.12
  5053.6 2179.91    5061 2184.99  5068.4 2188.27  5104.1 2189.03  5110.2 2188.21
  5118.9 2189.37    5125 2188.51  5133.8 2190.05  5146.4 2191.11    5183 2191.94
#Mann= 5 ,-1 , 0
  4778.5    .035       0  4798.6     .16       0  4997.1     .07       0
  5019.5     .07       0  5029.1     .07       0
Bank Sta=5019.5,5029.1
XS Rating Curve= 0 ,0
Exp/Cntr=0.3,0.1

Type RM Length L Ch R = 1 ,5985    ,553,553,553
BEGIN DESCRIPTION:
Idlewild Creek 10.0
END DESCRIPTION:
XS GIS Cut Line= 3
      1370754.98      6845437.98      1370684.69       6845357.7
      1370405.05      6845288.01
#Sta/Elev= 30
  4893.3  2195.2    4894  2195.2  4914.6 2194.29  4921.3 2193.54  4928.9 2193.45
  4935.5 2192.75  4943.1 2189.98  4949.7 2185.27  4957.3 2178.91    4964 2175.09
  4971.6 2172.89  4973.4 2169.32  4973.9 2168.82  4982.5 2168.82    4983 2169.32
  4992.5 2171.77  4996.5 2174.76    5010 2175.16  5017.3 2174.63  5030.6 2175.48
  5051.2 2175.79  5071.8  2178.3  5123.4 2182.42  5146.3 2183.82  5164.6 2185.58
  5174.9 2185.52  5195.5 2186.97  5205.8 2186.93    5265  2189.7  5288.2 2189.88
#Mann= 4 ,-1 , 0
  4893.3    .035       0    4894     .07       0  4973.4     .07       0
    4983     .07       0
Bank Sta=4973.4,4983
XS Rating Curve= 0 ,0
Exp/Cntr=0.3,0.1

Type RM Length L Ch R = 1 ,5432    ,181,181,181
BEGIN DESCRIPTION:
Idlewild Creek 9.0
END DESCRIPTION:
XS GIS Cut Line= 3
      1371191.68      6845032.91      1370961.18      6844936.12
      1370668.75      6844955.92
#Sta/Elev= 30
    4750 2210.75  4757.2 2208.43  4789.8 2204.06  4803.7 2201.12  4811.5 2198.39
  4822.1 2196.97  4833.2 2193.91  4865.7 2190.22  4887.4  2190.3  4904.2 2189.37
  4919.9 2184.84  4933.4 2172.59  4943.4 2169.21  4951.7  2167.1  4957.1 2167.12
  4963.3 2165.73    4976 2165.49  4976.5 2164.99  4985.9 2165.49  5026.2 2165.79
  5036.3 2167.63  5046.3    2171  5056.3 2176.49  5066.3 2178.39  5086.4 2178.59
  5101.6 2180.01  5106.7 2179.29  5186.6  2184.8  5216.7  2186.2  5293.1 2186.88
#Mann= 4 ,-1 , 0
    4750    .035       0  4943.4     .07       0    4976     .07       0
  4985.9     .07       0
Bank Sta=4976,4985.9
XS Rating Curve= 0 ,0
Exp/Cntr=0.3,0.1

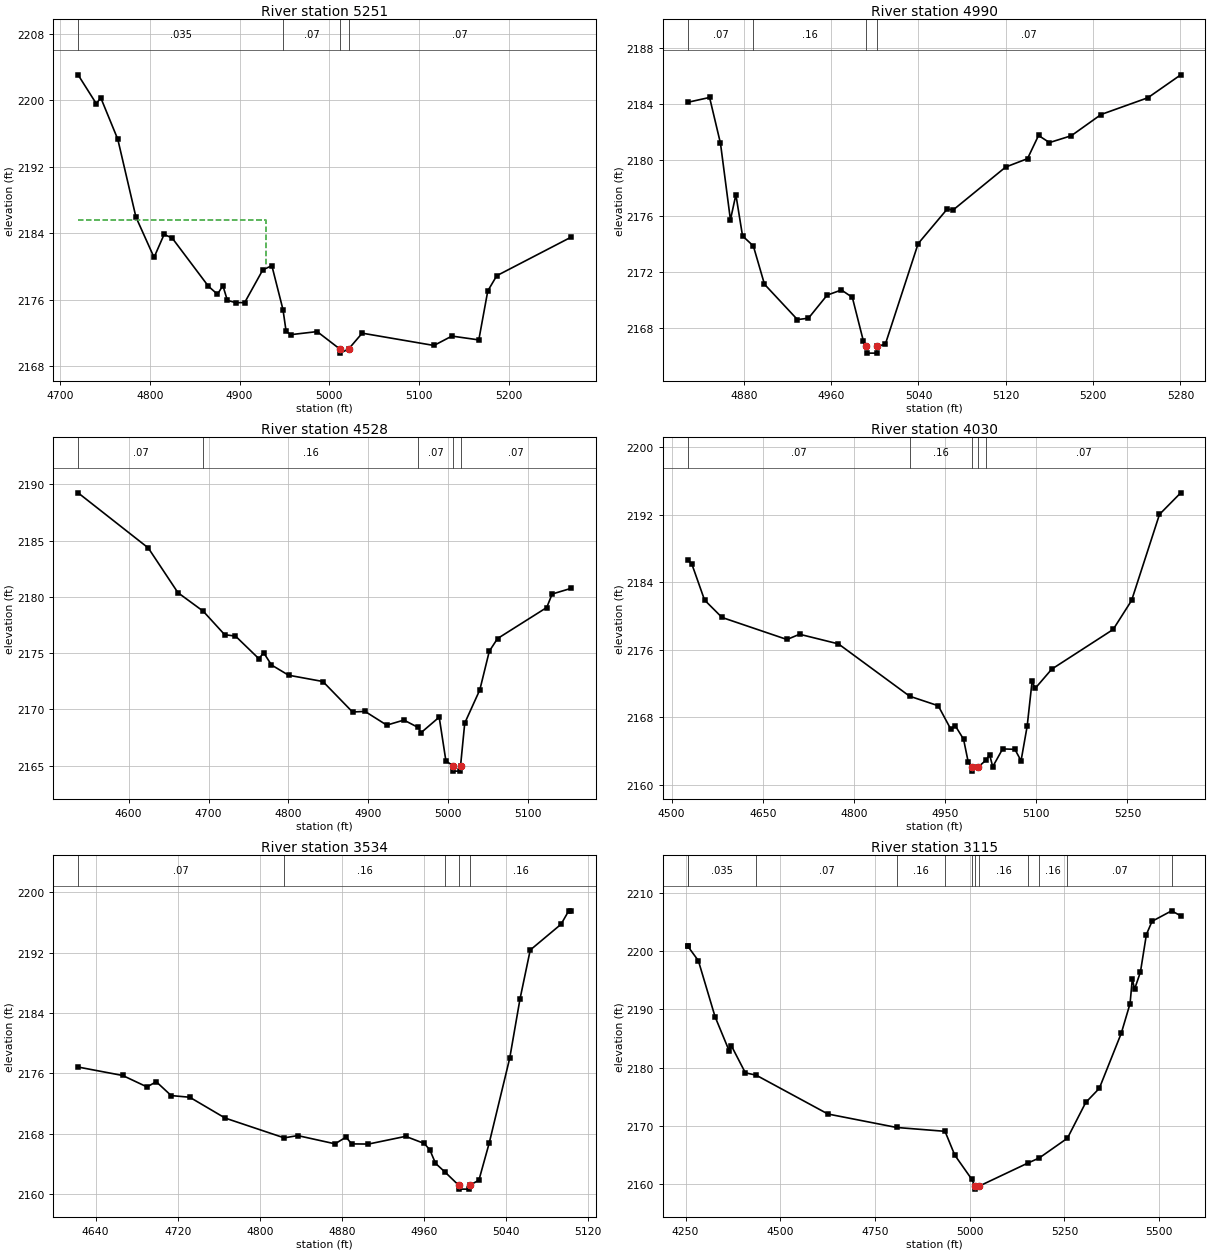
Type RM Length L Ch R = 1 ,5251    ,261,261,261
BEGIN DESCRIPTION:
Idlewild Creek 8.1
END DESCRIPTION:
XS GIS Cut Line= 3
      1371328.82      6844826.05      1371051.66      6844786.28
      1370781.86      6844787.66
#Sta/Elev= 30
    4720 2203.05  4740.3 2199.58  4745.3 2200.29  4764.3 2195.29  4784.5 2185.94
  4804.7 2181.09  4815.9 2183.86  4824.9 2183.42  4865.3 2177.62  4875.4 2176.66
  4881.4  2177.7  4886.4 2175.93  4895.6 2175.65  4905.7 2175.66  4925.9 2179.59
    4936  2180.1  4948.4 2174.82  4951.9  2172.2    4957  2171.8  4986.5 2172.17
  5011.7 2170.08  5012.2 2169.58  5021.6 2170.08  5036.7 2171.98  5116.7  2170.5
  5136.7 2171.63  5166.7 2171.17  5176.7 2177.06  5186.7 2178.89  5269.8 2183.54
#Mann= 4 ,-1 , 0
    4720    .035       0  4948.4     .07       0  5011.7     .07       0
  5021.6     .07       0
#XS Ineff= 2 , 0
         4929.64 2185.58
Permanent Ineff=
       F       F
Bank Sta=5011.7,5021.6
XS Rating Curve= 0 ,0
Exp/Cntr=0.3,0.1

Type RM Length L Ch R = 1 ,4990    ,462,462,462
BEGIN DESCRIPTION:
Idlewild Creek 8.0
END DESCRIPTION:
XS GIS Cut Line= 3
      1371105.03        6844588.      1370934.58      6844568.17
      1370654.98        6844588.
#Sta/Elev= 30
  4828.4 2184.14  4848.6 2184.49  4858.6  2181.2  4867.7 2175.73  4872.7 2177.53
  4878.8 2174.58  4888.7 2173.86  4898.9 2171.12  4929.1 2168.59  4939.2 2168.69
  4956.3 2170.34  4969.4 2170.71  4979.4 2170.18  4989.5 2167.06  4992.3 2166.69
  4992.8 2166.19  5001.8 2166.19  5002.3 2166.69  5009.6 2166.82  5039.7 2174.03
  5066.5 2176.52  5071.5 2176.42  5119.9 2179.51  5139.9 2180.11    5150 2181.77
    5160 2181.26    5180 2181.75  5207.3 2183.27  5250.2 2184.47  5280.3 2186.11
#Mann= 4 ,-1 , 0
  4828.4     .07       0  4888.7     .16       0  4992.3     .07       0
  5002.3     .07       0
Bank Sta=4992.3,5002.3
XS Rating Curve= 0 ,0
Exp/Cntr=0.3,0.1

Type RM Length L Ch R = 1 ,4528    ,498,498,498
BEGIN DESCRIPTION:
Idlewild Creek 7.0
END DESCRIPTION:
XS GIS Cut Line= 3
      1371205.02      6844388.01      1370805.51      6844153.22
      1370654.97      6844188.01
#Sta/Elev= 30
  4536.6 2189.25  4624.5 2184.35  4661.7 2180.37  4693.4 2178.72  4720.3 2176.63
  4733.8 2176.51  4763.2 2174.49    4769 2175.04  4778.9 2173.94  4800.3 2173.03
  4843.3 2172.47  4880.4 2169.76  4896.1 2169.81  4923.3 2168.59  4944.8 2169.04
  4962.7 2168.38  4966.3 2167.92    4989  2169.3  4997.4 2165.41  5005.8    2165
  5006.3  2164.5  5015.3  2164.5  5015.8    2165    5021 2168.77  5039.9 2171.73
  5051.8 2175.17  5062.1 2176.29  5123.7 2179.05  5130.5 2180.25  5154.5 2180.76
#Mann= 5 ,-1 , 0
  4536.6     .07       0  4693.4     .16       0  4962.7     .07       0
  5005.8     .07       0  5015.8     .07       0
Bank Sta=5005.8,5015.8
XS Rating Curve= 0 ,0
Exp/Cntr=0.3,0.1

Type RM Length L Ch R = 1 ,4030    ,496,496,496
BEGIN DESCRIPTION:
Idlewild Creek 6.0
END DESCRIPTION:
XS GIS Cut Line= 3
      1371255.03      6844038.03       1370889.2      6843736.94
      1370554.96      6843687.99
#Sta/Elev= 30
  4526.2 2186.68  4533.4 2186.14  4554.2  2181.9  4582.9 2179.84  4689.8 2177.23
  4710.6 2177.85  4774.5 2176.71  4891.6 2170.52  4938.7 2169.39  4959.6 2166.59
  4966.6 2167.04  4980.4 2165.43  4988.2 2162.68  4994.3 2162.15  4994.8 2161.65
  5004.7 2162.15  5017.2 2162.94  5023.3 2163.59  5028.4 2162.17  5044.7 2164.28
  5064.9 2164.23    5075 2162.87  5085.1 2166.98  5093.2  2172.3  5098.2 2171.44
  5125.5 2173.72  5226.6 2178.42  5256.9 2181.85  5302.8 2192.04  5337.8 2194.59
#Mann= 5 ,-1 , 0
  4526.2     .07       0  4891.6     .16       0  4994.3     .07       0
  5004.7     .16       0  5017.2     .07       0
Bank Sta=4994.3,5004.7
XS Rating Curve= 0 ,0
Exp/Cntr=0.3,0.1

Type RM Length L Ch R = 1 ,3534    ,419,419,419
BEGIN DESCRIPTION:
Idlewild Creek 5.0
END DESCRIPTION:
XS GIS Cut Line= 3
      1371155.01      6843638.02      1371006.46      6843291.52
        1371005.      6843188.03
#Sta/Elev= 30
    4623 2176.84  4666.5 2175.72  4690.1 2174.21  4699.2 2174.89  4713.7 2173.06
  4731.8 2172.84  4766.3 2170.08  4823.8 2167.46    4837 2167.76  4873.3 2166.67
  4884.1 2167.56  4889.5 2166.66  4905.9 2166.64  4942.1 2167.66  4960.2 2166.72
  4965.7 2165.87  4971.2 2164.09  4980.7  2162.9  4993.9 2161.17  4994.4 2160.67
    5004 2160.67  5004.5 2161.17  5013.5 2161.86  5023.5 2166.76  5043.5 2178.01
  5053.5 2185.84  5063.5 2192.34  5093.5 2195.75    5101 2197.53  5103.5 2197.53
#Mann= 5 ,-1 , 0
    4623     .07       0  4823.8     .16       0  4980.7     .07       0
  4993.9     .07       0  5004.5     .16       0
Bank Sta=4993.9,5004.5
XS Rating Curve= 0 ,0
Exp/Cntr=0.3,0.1

Type RM Length L Ch R = 1 ,3115    ,181,181,181
BEGIN DESCRIPTION:
Idlewild Creek 4.1
END DESCRIPTION:
XS GIS Cut Line= 3
      1371788.96      6843972.58       1371407.7      6843332.64
      1371125.26      6842852.68
#Sta/Elev= 30
  4255.1 2200.84  4255.6 2200.84  4283.7 2198.34  4327.8 2188.72  4364.8  2182.9
  4370.7 2183.76  4407.7  2179.1  4436.2  2178.7  4625.7 2172.03  4807.1 2169.72
  4934.7 2169.06  4960.5 2164.97  5004.9 2160.87  5013.6 2159.64  5014.1 2159.14
  5024.3 2159.64  5154.2 2163.64    5183 2164.47  5257.8 2167.88  5306.1 2174.01
  5341.9 2176.43  5399.9 2185.89  5423.1 2190.98  5429.1 2195.25  5434.9 2193.43
  5450.5 2196.41  5466.2 2202.83  5481.1  2205.1  5532.8  2206.9  5556.9 2206.04
#Mann= 12 ,-1 , 0
  4255.1     .07       0  4255.6    .035       0  4436.2     .07       0
  4807.1     .16       0  4934.7     .07       0  5004.9     .16       0
  5013.6     .07       0  5024.3     .16       0  5154.2     .07       0
    5183     .16       0  5257.8     .07       0  5532.8    .035       0
Bank Sta=5013.6,5024.3
XS Rating Curve= 0 ,0
Exp/Cntr=0.3,0.1

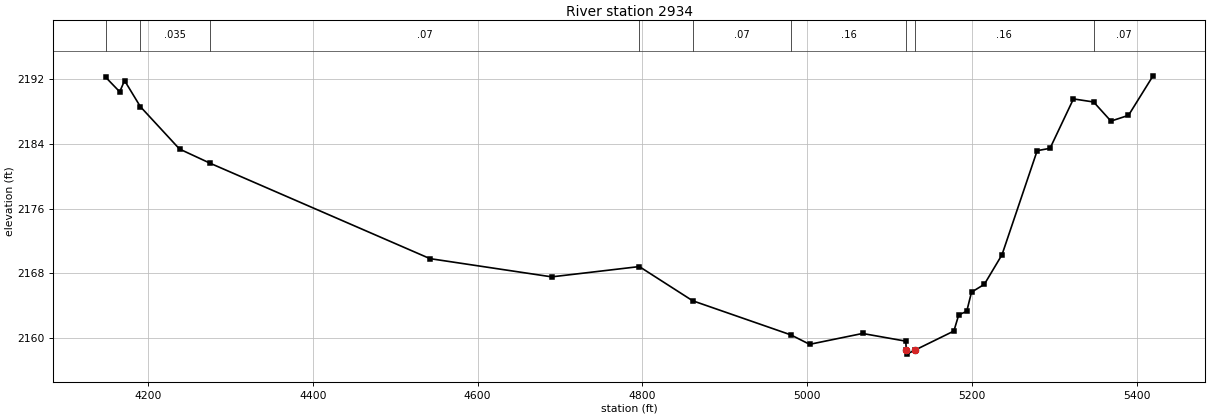
Type RM Length L Ch R = 1 ,2934    ,393,393,393
BEGIN DESCRIPTION:
Idlewild Creek 4.0
END DESCRIPTION:
XS GIS Cut Line= 3
      1371940.64       6843914.4      1371839.87      6843749.17
      1371286.11      6842825.13
#Sta/Elev= 30
  4148.8  2192.2  4165.7 2190.42  4171.6  2191.8  4190.8 2188.58  4238.3 2183.35
  4275.8 2181.58  4542.2 2169.82  4689.9 2167.57  4796.2 2168.84  4860.9 2164.62
    4980 2160.41  5002.9 2159.24  5067.1 2160.58  5119.6 2159.63  5120.1 2158.53
  5120.6 2158.03  5130.8 2158.53  5177.9 2160.88  5183.8 2162.88  5193.5 2163.31
  5199.3 2165.68  5214.9 2166.65  5236.3  2170.3    5279 2183.15  5294.6 2183.44
    5323 2189.54  5347.5 2189.16  5368.5  2186.8  5389.8 2187.51  5419.6 2192.39
#Mann= 9 ,-1 , 0
  4148.8     .07       0  4190.8    .035       0  4275.8     .07       0
  4796.2     .16       0  4860.9     .07       0    4980     .16       0
  5120.1     .07       0  5130.8     .16       0  5347.5     .07       0
Bank Sta=5120.1,5130.8
XS Rating Curve= 0 ,0
Exp/Cntr=0.3,0.1