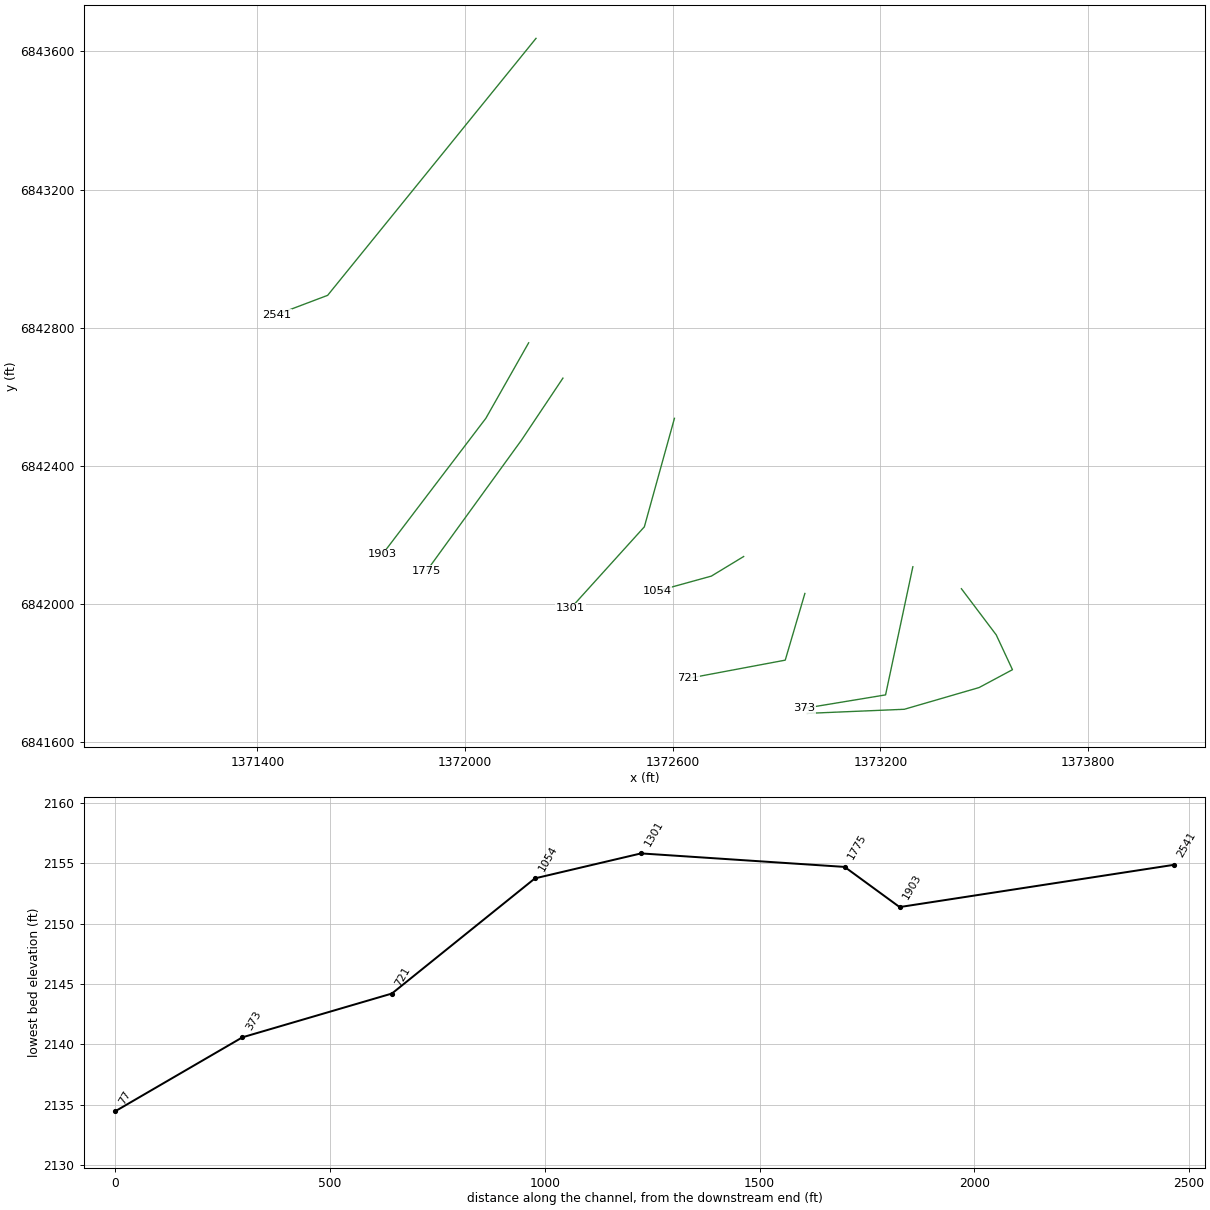
HEC-RAS study Idlewild Creek.prj: Idlewild Creek Base Level Engineering

--- Idlewild Creek.g01 (geometry) --- (continued)

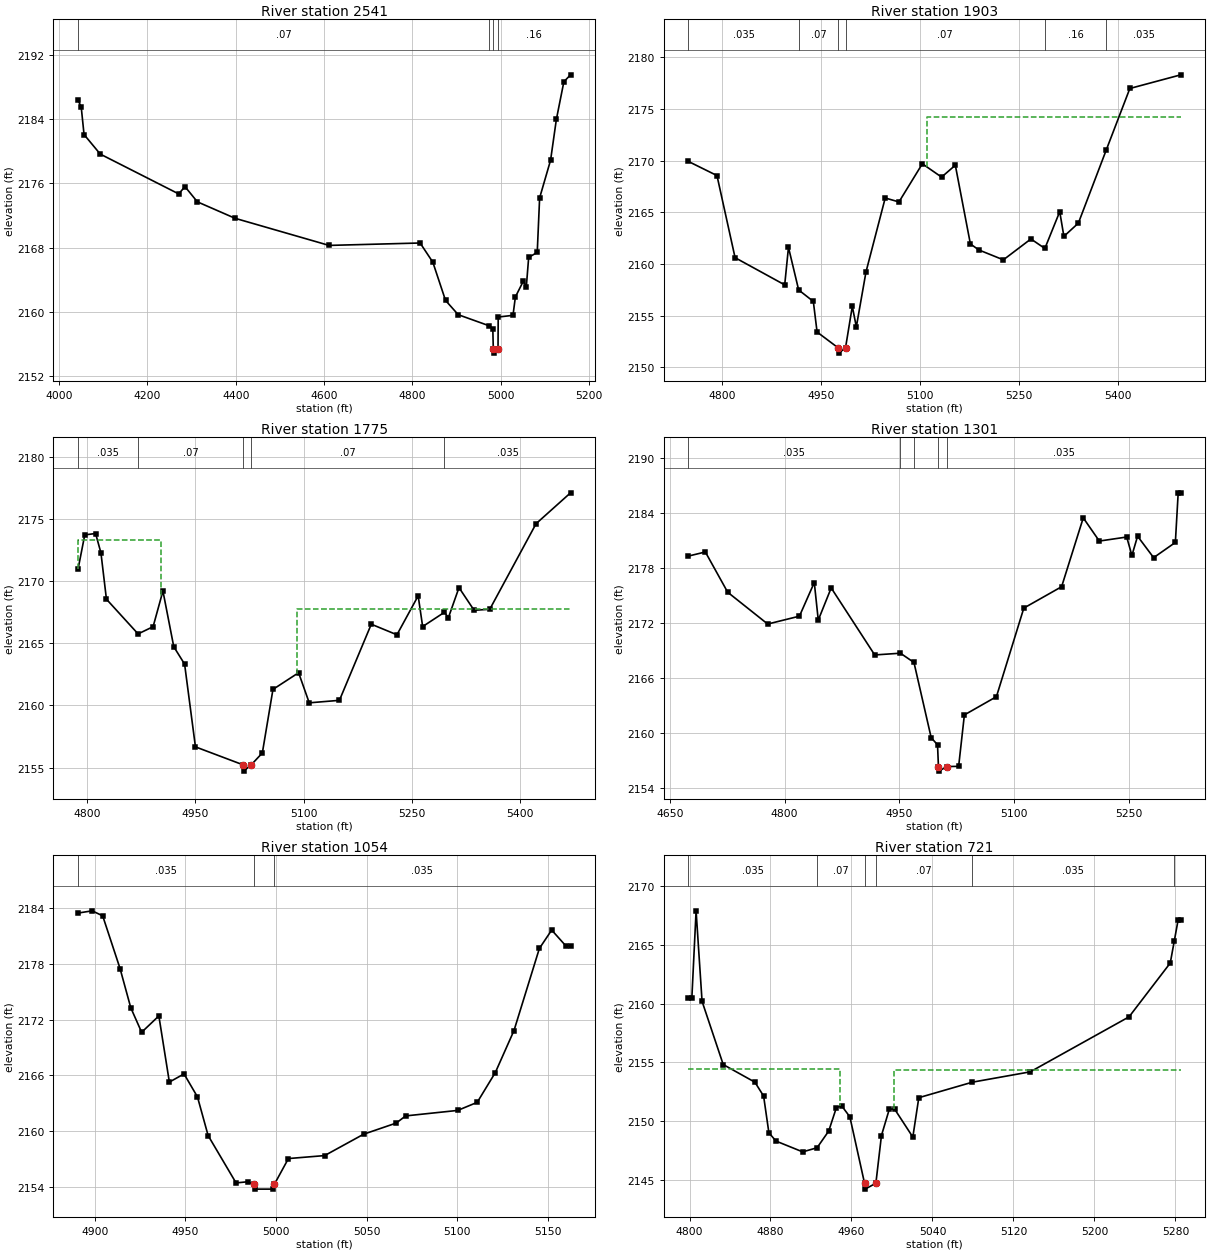
Type RM Length L Ch R = 1 ,2541    ,638,638,638
BEGIN DESCRIPTION:
Idlewild Creek 3.0
END DESCRIPTION:
XS GIS Cut Line= 3
        1372205.      6843637.99      1371602.81      6842894.08
      1371454.99        6842838.
#Sta/Elev= 30
  4042.9 2186.36  4050.1 2185.49  4056.5 2182.07  4093.2 2179.64  4270.7 2174.69
  4285.1 2175.59  4313.1  2173.7  4398.6 2171.65  4611.3 2168.28  4817.5 2168.58
  4846.3 2166.19    4875 2161.44  4903.8 2159.66  4973.9 2158.28  4982.1 2157.94
  4983.2 2155.38  4983.7 2154.88  4993.9 2155.38  4994.3 2159.37  5027.8 2159.58
  5033.2 2161.87  5051.1 2163.82    5058 2163.15  5063.3 2166.79  5082.7 2167.41
  5088.1 2174.19  5112.9 2178.88    5126 2183.95    5143 2188.64  5158.1  2189.5
#Mann= 4 ,-1 , 0
  4042.9     .07       0  4973.9     .16       0  4983.2     .07       0
  4993.9     .16       0
Bank Sta=4983.2,4993.9
XS Rating Curve= 0 ,0
Exp/Cntr=0.3,0.1

Type RM Length L Ch R = 1 ,1903    ,128,128,128
BEGIN DESCRIPTION:
Idlewild Creek 2.1
END DESCRIPTION:
XS GIS Cut Line= 3
      1372183.69      6842756.69      1372060.17      6842538.41
      1371761.19      6842144.54
#Sta/Elev= 30
  4749.2 2169.92  4792.6 2168.55    4820 2160.61  4895.1 2157.98  4900.8 2161.61
  4916.2 2157.49  4938.4 2156.38  4944.1 2153.42  4976.2 2151.88  4976.7 2151.38
  4987.1 2151.88  4997.4  2155.9  5003.5 2153.92  5018.1 2159.23  5047.2 2166.38
    5068    2166  5103.4 2169.69  5132.5  2168.4  5153.3 2169.55  5176.1 2161.94
  5188.8 2161.36    5226  2160.4  5267.7 2162.42  5288.8  2161.5  5311.3 2165.06
  5317.6 2162.67  5339.5 2163.95  5381.8 2171.04  5417.4 2176.97  5494.5 2178.29
#Mann= 6 ,-1 , 0
  4749.2    .035       0  4916.2     .07       0  4976.2     .07       0
  4987.1     .07       0  5288.8     .16       0  5381.8    .035       0
#XS Ineff= 2 , 0
                         5110.96          2174.2
Permanent Ineff=
       F       F
Bank Sta=4976.2,4987.1
XS Rating Curve= 0 ,0
Exp/Cntr=0.3,0.1

Type RM Length L Ch R = 1 ,1775    ,474,474,474
BEGIN DESCRIPTION:
Idlewild Creek 2.0
END DESCRIPTION:
XS GIS Cut Line= 3
      1372282.73       6842654.4       1372162.9      6842474.82
      1371889.79      6842097.47
#Sta/Elev= 30
  4787.7 2170.94    4797  2173.7    4812 2173.81  4819.4 2172.25    4827 2168.53
  4870.8 2165.74  4891.6 2166.32  4905.2 2169.19  4920.2 2164.71  4935.2 2163.31
  4950.2 2156.66  5016.4 2155.21  5016.9 2154.71  5027.3 2155.21  5042.8 2156.17
  5057.5 2161.28    5093 2162.62  5107.7  2160.2  5149.5  2160.4  5193.6 2166.52
  5229.1 2165.67  5258.5  2168.8  5264.7 2166.33  5294.9 2167.48  5300.3 2167.04
    5315 2169.46  5335.9 2167.64  5357.6 2167.72  5421.7  2174.6  5469.4 2177.08
#Mann= 5 ,-1 , 0
  4787.7    .035       0  4870.8     .07       0  5016.4     .07       0
  5027.3     .07       0  5294.9    .035       0
#XS Ineff= 2 , 0
         4903.05 2173.27 5090.66         2167.72
Permanent Ineff=
       F       F
Bank Sta=5016.4,5027.3
XS Rating Curve= 0 ,0
Exp/Cntr=0.3,0.1

Type RM Length L Ch R = 1 ,1301    ,247,247,247
BEGIN DESCRIPTION:
Idlewild Creek 1.0
END DESCRIPTION:
XS GIS Cut Line= 3
        1372605.        6842538.      1372518.06      6842224.02
      1372304.98      6841987.97
#Sta/Elev= 30
  4674.2 2179.28  4696.5 2179.73  4725.7 2175.34    4778 2171.87  4819.5 2172.73
  4838.9  2176.4  4844.1  2172.3    4861 2175.81  4917.9  2168.5  4951.5 2168.69
  4969.2 2167.68  4991.7 2159.48    5000  2158.7  5001.2 2156.33  5001.7 2155.83
  5012.3 2156.33  5027.6 2156.35  5035.1 2161.96    5077 2163.95  5112.8 2173.61
  5162.2 2175.94  5190.5 2183.45  5211.5 2180.92  5247.3 2181.36  5254.1 2179.35
  5261.5 2181.45  5282.5 2179.11  5310.9 2180.77  5314.6 2186.18    5318 2186.18
#Mann= 5 ,-1 , 0
  4674.2    .035       0  4951.5     .07       0  4969.2    .035       0
  5001.2    .035       0  5012.3    .035       0
Bank Sta=5001.2,5012.3
XS Rating Curve= 0 ,0
Exp/Cntr=0.3,0.1

Type RM Length L Ch R = 1 ,1054    ,333,333,333
BEGIN DESCRIPTION:
Idlewild Creek 0.3
END DESCRIPTION:
XS GIS Cut Line= 3
      1372805.01      6842138.01      1372711.67      6842081.34
      1372554.96      6842037.99
#Sta/Elev= 30
  4890.8 2183.47  4898.6 2183.71  4904.4 2183.17    4914 2177.49  4919.9 2173.28
  4925.9 2170.64  4935.4  2172.4  4941.2 2165.28  4949.3 2166.16  4956.7 2163.69
  4962.6 2159.52    4978 2154.43  4984.4 2154.55    4988 2154.26  4988.5 2153.76
  4998.6 2153.76  4999.1 2154.26  5006.9 2157.05  5026.9 2157.37  5048.4 2159.67
  5066.4 2160.87  5071.6 2161.64  5100.3 2162.23  5111.1  2163.1  5121.1 2166.31
  5131.4 2170.83  5145.4 2179.66  5152.2 2181.64    5160 2179.94  5162.6 2179.94
#Mann= 3 ,-1 , 0
  4890.8    .035       0    4988    .035       0  4999.1    .035       0
Bank Sta=4988,4999.1
XS Rating Curve= 0 ,0
Exp/Cntr=0.3,0.1

Type RM Length L Ch R = 1 ,721     ,348,348,348
BEGIN DESCRIPTION:
Idlewild Creek 0.2
END DESCRIPTION:
XS GIS Cut Line= 3
      1372981.95      6842031.09       1372925.2      6841838.06
      1372644.81      6841785.34
#Sta/Elev= 30
  4798.8 2160.45  4802.3 2160.45  4806.5 2167.89  4812.4 2160.19  4833.3 2154.81
  4864.6 2153.31  4873.2 2152.13  4878.4 2149.01  4885.4  2148.3  4911.8 2147.38
    4926 2147.73  4937.5 2149.15  4945.1 2151.15  4950.3  2151.3  4958.4 2150.36
  4972.9 2144.71  4973.4 2144.21  4984.1 2144.71  4989.6 2148.77  4997.4 2151.02
  5002.6 2151.02  5020.6 2148.64  5026.5 2151.99  5079.4 2153.31  5136.6 2154.19
  5234.2 2158.87  5274.9 2163.45  5278.9 2165.34  5282.7 2167.13  5285.3 2167.13
#Mann= 6 ,-1 , 0
  4798.8    .035       0    4926     .07       0  4972.9     .07       0
  4984.1     .07       0  5079.4    .035       0  5278.9     .07       0
#XS Ineff= 2 , 0
         4948.53 2154.44 5001.52         2154.32
Permanent Ineff=
       F       F
Bank Sta=4972.9,4984.1
XS Rating Curve= 0 ,0
Exp/Cntr=0.3,0.1

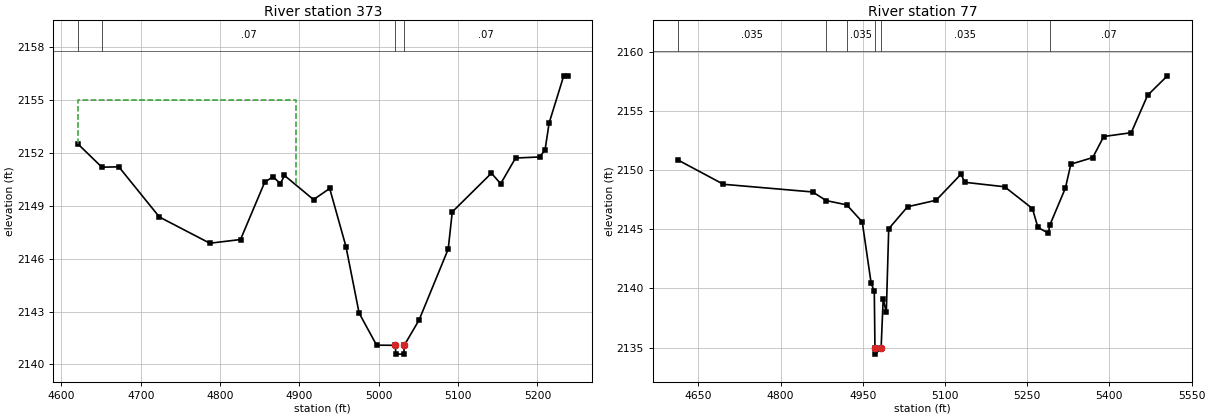
Type RM Length L Ch R = 1 ,373     ,296,296,296
BEGIN DESCRIPTION:
Idlewild Creek 0.1
END DESCRIPTION:
XS GIS Cut Line= 3
        1373294.      6842108.49      1373215.12      6841737.48
      1372980.21      6841698.64
#Sta/Elev= 30
  4620.7 2152.52  4650.9  2151.2  4672.3 2151.22  4723.4 2148.37    4787 2146.88
  4825.7 2147.09  4856.3 2150.36  4866.6 2150.65    4876 2150.27  4881.1 2150.73
  4917.7 2149.36  4938.1 2149.99  4958.6 2146.69  4975.2 2142.91  4997.2 2141.09
  5020.9 2141.08  5021.4 2140.58  5031.6 2140.58  5032.1 2141.08  5050.8 2142.52
  5087.5 2146.55  5092.6 2148.66    5142 2150.86  5153.6 2150.26  5172.4 2151.72
  5202.8 2151.78  5209.6 2152.19  5214.7 2153.71  5233.1 2156.39  5238.1 2156.39
#Mann= 4 ,-1 , 0
  4620.7    .035       0  4650.9     .07       0  5020.9     .07       0
  5032.1     .07       0
#XS Ineff= 2 , 0
         4895.63    2155
Permanent Ineff=
       F       F
Bank Sta=5020.9,5032.1
XS Rating Curve= 0 ,0
Exp/Cntr=0.3,0.1

Type RM Length L Ch R = 1 ,77      ,0,0,0
BEGIN DESCRIPTION:
Idlewild Creek 4468
END DESCRIPTION:
XS GIS Cut Line= 6
       1373434.3      6842044.78      1373534.96      6841911.14
      1373581.84      6841810.44       1373485.5      6841758.78
      1373269.34      6841695.86      1372989.03        6841684.
#Sta/Elev= 30
  4612.3 2150.88  4695.9 2148.81  4858.7 2148.16  4883.4 2147.43  4920.9 2147.07
  4949.1 2145.63  4965.4 2140.43  4971.1 2139.77  4972.3 2134.95  4972.8 2134.45
  4983.5 2134.95  4987.3 2139.13    4993 2137.97  4997.4 2145.05  5031.8 2146.91
  5083.8 2147.46  5129.4 2149.67  5135.9 2148.98  5208.8  2148.6  5259.5 2146.76
  5269.5 2145.17  5288.7 2144.67    5291 2145.33  5319.6 2148.48  5329.6 2150.51
  5369.6 2151.07  5389.6 2152.85  5439.7 2153.17  5469.7 2156.34  5505.7 2157.98
#Mann= 6 ,-1 , 0
  4612.3    .035       0  4883.4     .16       0  4920.9    .035       0
  4972.3     .07       0  4983.5    .035       0    5291     .07       0
Bank Sta=4972.3,4983.5
XS Rating Curve= 0 ,0
Exp/Cntr=0.3,0.1

Chan Stop Cuts=-1
Use User Specified Reach Order=0
Composite Channel Slope=5