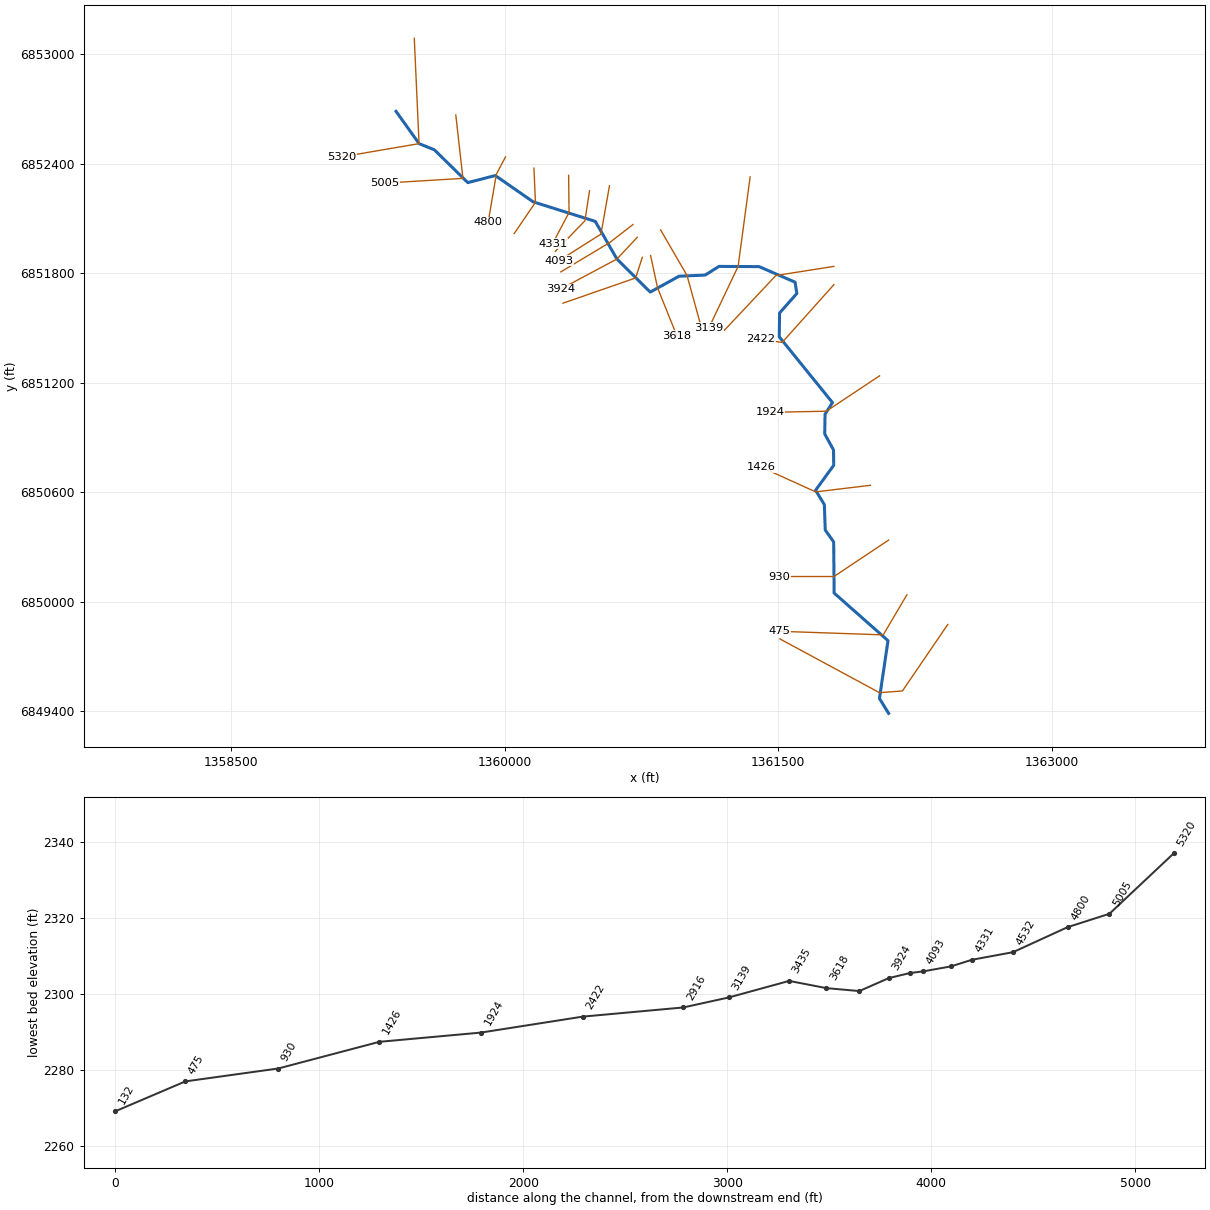
--- Idlewild Creek Trib1.prj (project) ---

Proj Title=Idlewild Creek Trib1 Base Level Engineering
Current Plan=p01
Default Exp/Contr=0.3,0.1
English Units
Geom File=g01
Flow File=f01
Plan File=p01
Y Axis Title=Elevation
X Axis Title(PF)=Main Channel Distance
X Axis Title(XS)=Station
BEGIN DESCRIPTION:
Idlewild Creek Trib1
END DESCRIPTION:
DSS Export Rating Curves= 0
DSS Export Rating Curve Sorted= 0
DSS Export Volume Flow Curves= 0
DXF OffsetX= 0
DXF OffsetY= 0
DXF ScaleX= 1
DXF ScaleY= 10

--- Idlewild Creek Trib1.p01 (plan) ---

Plan Title=Multiple Run
Short Identifier=Multiple
Geom File=g01
Flow File=f01
Subcritical Flow
K Sum by GR= 0
Std Step Tol= 0.01
Critical Tol= 0.01
Num of Std Step Trials= 20
Max Error Tol= 0.3
Flow Tol Ratio= 0.001
Split Flow NTrial= 30
Split Flow Tol= 0.02
Split Flow Ratio= 0.02
Log Output Level= 0
Friction Slope Method= 1
Unsteady Friction Slope Method= 2
Unsteady Bridges Friction Slope Method= 1
Parabolic Critical Depth
Global Vel Dist=  1 , 1 , 1
Global Log Level= 0
CheckData=True
Encroach Param= -1, 0, 0, 0
BEGIN DESCRIPTION:
Multiple Run
END DESCRIPTION:

--- Idlewild Creek Trib1.f01 (steady flow) ---

Flow Title=Multiple
Program Version=4.10
Number of Profiles= 7
Profile Names=10-year,25-year,50-year,1pct_min,100-year,1pct_plu,500-year
River Rch & RM=Idlewild Creek T,Reach-1         ,5320
     243     346     433     270     539    1076     845
River Rch & RM=Idlewild Creek T,Reach-1         ,132
     450     659     839     530    1058    2112    1710
Boundary for River Rch & Prof#=Idlewild Creek T,Reach-1         , 1
Up Type= 0
Dn Type= 3
Dn Slope=0.023
Boundary for River Rch & Prof#=Idlewild Creek T,Reach-1         , 2
Up Type= 0
Dn Type= 3
Dn Slope=0.023
Boundary for River Rch & Prof#=Idlewild Creek T,Reach-1         , 3
Up Type= 0
Dn Type= 3
Dn Slope=0.023
Boundary for River Rch & Prof#=Idlewild Creek T,Reach-1         , 4
Up Type= 0
Dn Type= 3
Dn Slope=0.023
Boundary for River Rch & Prof#=Idlewild Creek T,Reach-1         , 5
Up Type= 0
Dn Type= 3
Dn Slope=0.023
Boundary for River Rch & Prof#=Idlewild Creek T,Reach-1         , 6
Up Type= 0
Dn Type= 3
Dn Slope=0.023
Boundary for River Rch & Prof#=Idlewild Creek T,Reach-1         , 7
Up Type= 0
Dn Type= 3
Dn Slope=0.023
DSS Import GetInterval= 0
DSS Import GetPeak= 0
DSS Import FillOption= 0

--- Idlewild Creek Trib1.g01 (geometry) ---

Geom Title=Existing Conditions

River Reach=Idlewild Creek T,Reach-1
Reach XY= 30
      1359405.00      6852688.00      1359531.16      6852510.86
      1359614.66      6852477.21      1359798.26      6852297.13
      1359949.10      6852336.02      1360156.58      6852191.83
      1360496.95      6852084.68      1360615.78      6851878.32
      1360798.27      6851697.11      1360956.56      6851784.24
      1361099.47      6851790.39      1361175.03      6851837.93
      1361394.50      6851836.78      1361592.06      6851751.63
      1361601.91      6851689.68      1361507.17      6851582.55
      1361505.52      6851451.86      1361797.21      6851091.42
      1361756.54      6851028.41      1361754.58      6850919.67
      1361802.84      6850832.02      1361803.90      6850747.64
      1361704.54      6850610.84      1361752.70      6850532.07
      1361757.39      6850393.53      1361803.78      6850327.50
      1361806.20      6850047.59      1362101.55      6849786.52
      1362054.61      6849469.66      1362105.00      6849388.00

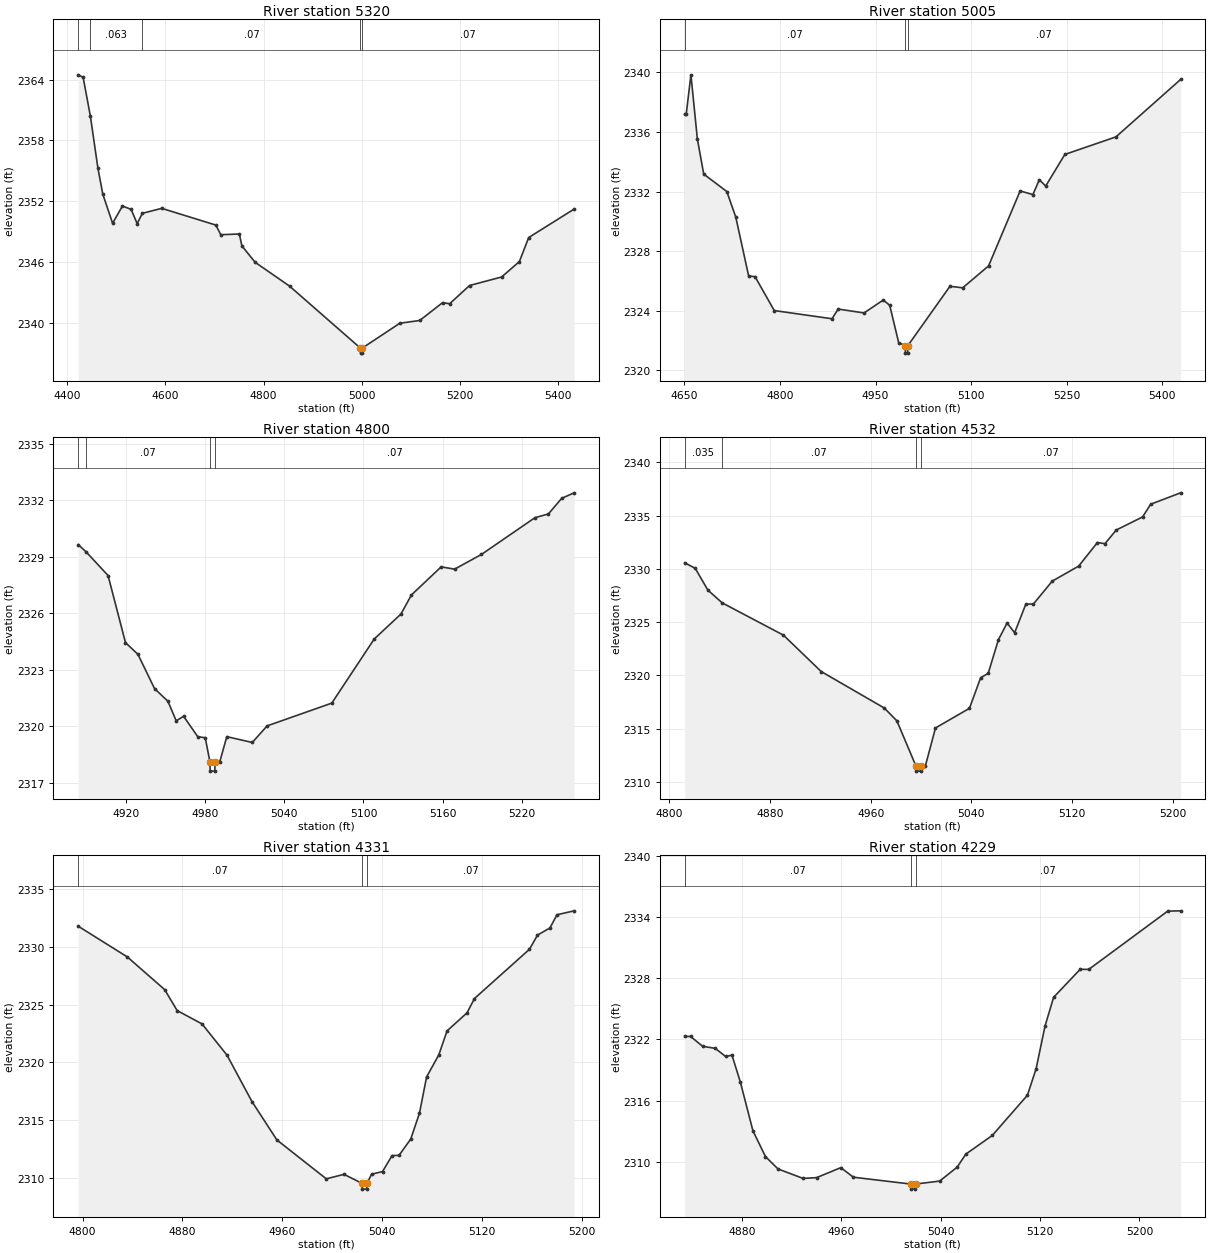
Type RM Length L Ch R = 1,5320,315,315,315
BEGIN DESCRIPTION:
Idlewild Creek Trib1 10.0
END DESCRIPTION:
XS GIS Cut Line= 3
      1359505.00      6853087.97      1359531.16      6852510.86
      1359105.05      6852438.01
#Sta/Elev= 30
  4422.3 2364.47  4432.3 2364.22  4447.1 2360.39  4462.3 2355.30  4472.3 2352.71
  4492.3 2349.83  4512.4 2351.53  4530.0 2351.20  4542.4 2349.79  4552.9 2350.81
  4592.4 2351.30  4702.6 2349.65  4712.6 2348.70  4750.5 2348.77  4755.6 2347.60
  4782.6 2345.98  4852.7 2343.63  4996.9 2337.52  4997.2 2337.02  5000.7 2337.02
  5000.9 2337.52  5077.3 2339.97  5117.8 2340.24  5164.4 2342.00  5178.7 2341.89
  5219.3 2343.69  5284.6 2344.53  5320.8 2346.05  5339.7 2348.42  5432.3 2351.23
#Mann=5,-1,0
  4422.3   0.094       0  4447.1   0.063       0  4552.9    0.07       0
  4996.9    0.07       0  5000.9    0.07       0
Bank Sta=4996.9,5000.9
Exp/Cntr=0.3,0.1

Type RM Length L Ch R = 1,5005,205,205,205
BEGIN DESCRIPTION:
Idlewild Creek Trib1 4424
END DESCRIPTION:
XS GIS Cut Line= 3
      1359732.49      6852667.74      1359771.65      6852320.44
      1359343.64      6852294.48
#Sta/Elev= 30
  4650.5 2337.19  4652.9 2337.19  4660.3 2339.84  4670.4 2335.53  4680.4 2333.17
  4716.6 2332.00  4730.7 2330.28  4750.9 2326.32  4760.9 2326.28  4791.1 2324.00
  4881.7 2323.45  4891.4 2324.10  4932.0 2323.84  4962.2 2324.71  4972.3 2324.35
  4986.3 2321.85  4996.7 2321.64  4997.0 2321.14  5000.5 2321.14  5000.7 2321.64
  5066.8 2325.63  5086.8 2325.53  5127.4 2327.00  5177.0 2332.04  5197.0 2331.79
  5207.0 2332.79  5217.1 2332.37  5247.1 2334.49  5327.3 2335.67  5428.8 2339.53
#Mann=3,-1,0
  4650.5    0.07       0  4996.7    0.07       0  5000.7    0.07       0
Bank Sta=4996.7,5000.7
Exp/Cntr=0.3,0.1

Type RM Length L Ch R = 1,4800,268,268,268
BEGIN DESCRIPTION:
Idlewild Creek Trib1 9.0
END DESCRIPTION:
XS GIS Cut Line= 3
      1360004.99      6852437.99      1359954.81      6852343.23
      1359909.79      6852078.76
#Sta/Elev= 30
  4884.0 2329.64  4889.8 2329.27  4906.6 2328.00  4919.8 2324.44  4929.2 2323.82
  4941.8 2322.00  4951.9 2321.33  4958.2 2320.29  4963.8 2320.53  4974.5 2319.45
  4980.2 2319.39  4983.7 2318.12  4983.9 2317.62  4987.4 2317.62  4987.7 2318.12
  4991.2 2318.12  4996.5 2319.45  5015.8 2319.14  5027.0 2320.02  5076.0 2321.23
  5108.1 2324.63  5128.4 2325.96  5136.3 2326.97  5158.8 2328.46  5169.0 2328.34
  5189.3 2329.12  5229.8 2331.07  5240.0 2331.27  5250.1 2332.10  5259.5 2332.39
#Mann=4,-1,0
  4884.0   0.035       0  4889.8    0.07       0  4983.7    0.07       0
  4987.7    0.07       0
Bank Sta=4983.7,4987.7
Exp/Cntr=0.3,0.1

Type RM Length L Ch R = 1,4532,201,201,201
BEGIN DESCRIPTION:
Idlewild Creek Trib1 4420
END DESCRIPTION:
XS GIS Cut Line= 3
      1360160.91      6852376.43      1360168.97      6852188.80
      1360052.83      6852018.30
#Sta/Elev= 30
  4812.2 2330.57  4820.6 2330.05  4830.6 2328.01  4842.0 2326.81  4890.7 2323.78
  4920.7 2320.37  4970.8 2316.95  4980.8 2315.75  4995.9 2311.53  4996.1 2311.03
  4999.6 2311.03  4999.9 2311.53  5003.5 2311.53  5011.5 2315.08  5038.5 2316.92
  5047.4 2319.79  5053.4 2320.20  5061.5 2323.35  5068.4 2324.92  5074.4 2324.01
  5083.3 2326.69  5089.3 2326.70  5104.3 2328.85  5125.3 2330.26  5140.2 2332.47
  5146.2 2332.36  5155.1 2333.64  5176.1 2334.87  5182.5 2336.06  5206.3 2337.13
#Mann=4,-1,0
  4812.2   0.035       0  4842.0    0.07       0  4995.9    0.07       0
  4999.9    0.07       0
Bank Sta=4995.9,4999.9
Exp/Cntr=0.3,0.1

Type RM Length L Ch R = 1,4331,102,102,102
BEGIN DESCRIPTION:
Idlewild Creek Trib1 8.0
END DESCRIPTION:
XS GIS Cut Line= 3
      1360351.02      6852337.30      1360353.27      6852133.81
      1360262.98      6851961.99
#Sta/Elev= 30
  4796.5 2331.77  4835.8 2329.12  4865.8 2326.29  4875.8 2324.48  4895.8 2323.32
  4915.8 2320.62  4935.8 2316.61  4955.8 2313.29  4995.4 2309.93  5009.6 2310.32
  5024.0 2309.54  5024.3 2309.04  5027.8 2309.04  5028.0 2309.54  5031.7 2310.33
  5040.5 2310.56  5048.1 2311.94  5053.7 2311.96  5063.1 2313.37  5070.1 2315.61
  5075.8 2318.74  5085.6 2320.65  5092.2 2322.72  5108.2 2324.28  5114.2 2325.52
  5158.3 2329.78  5164.7 2331.00  5174.7 2331.62  5180.3 2332.76  5194.1 2333.10
#Mann=3,-1,0
  4796.5    0.07       0  5024.0    0.07       0  5028.0    0.07       0
Bank Sta=5024,5028
Exp/Cntr=0.3,0.1

Type RM Length L Ch R = 1,4229,136,136,136
BEGIN DESCRIPTION:
Idlewild Creek Trib1 4422
END DESCRIPTION:
XS GIS Cut Line= 3
      1360465.53      6852252.32      1360440.20      6852087.97
      1360278.07      6851920.35
#Sta/Elev= 30
  4833.7 2322.30  4838.4 2322.30  4848.2 2321.33  4858.3 2321.13  4866.7 2320.33
  4871.8 2320.46  4878.5 2317.84  4888.7 2313.03  4898.8 2310.50  4908.9 2309.29
  4929.1 2308.36  4940.0 2308.44  4959.5 2309.42  4969.6 2308.48  5015.7 2307.81
  5016.0 2307.31  5019.5 2307.31  5019.7 2307.81  5039.1 2308.10  5053.2 2309.47
  5060.2 2310.75  5081.5 2312.58  5109.8 2316.53  5116.8 2319.13  5124.0 2323.33
  5130.9 2326.14  5152.3 2328.89  5159.2 2328.88  5222.8 2334.60  5233.2 2334.63
#Mann=3,-1,0
  4833.7    0.07       0  5015.7    0.07       0  5019.7    0.07       0
Bank Sta=5015.7,5019.7
Exp/Cntr=0.3,0.1

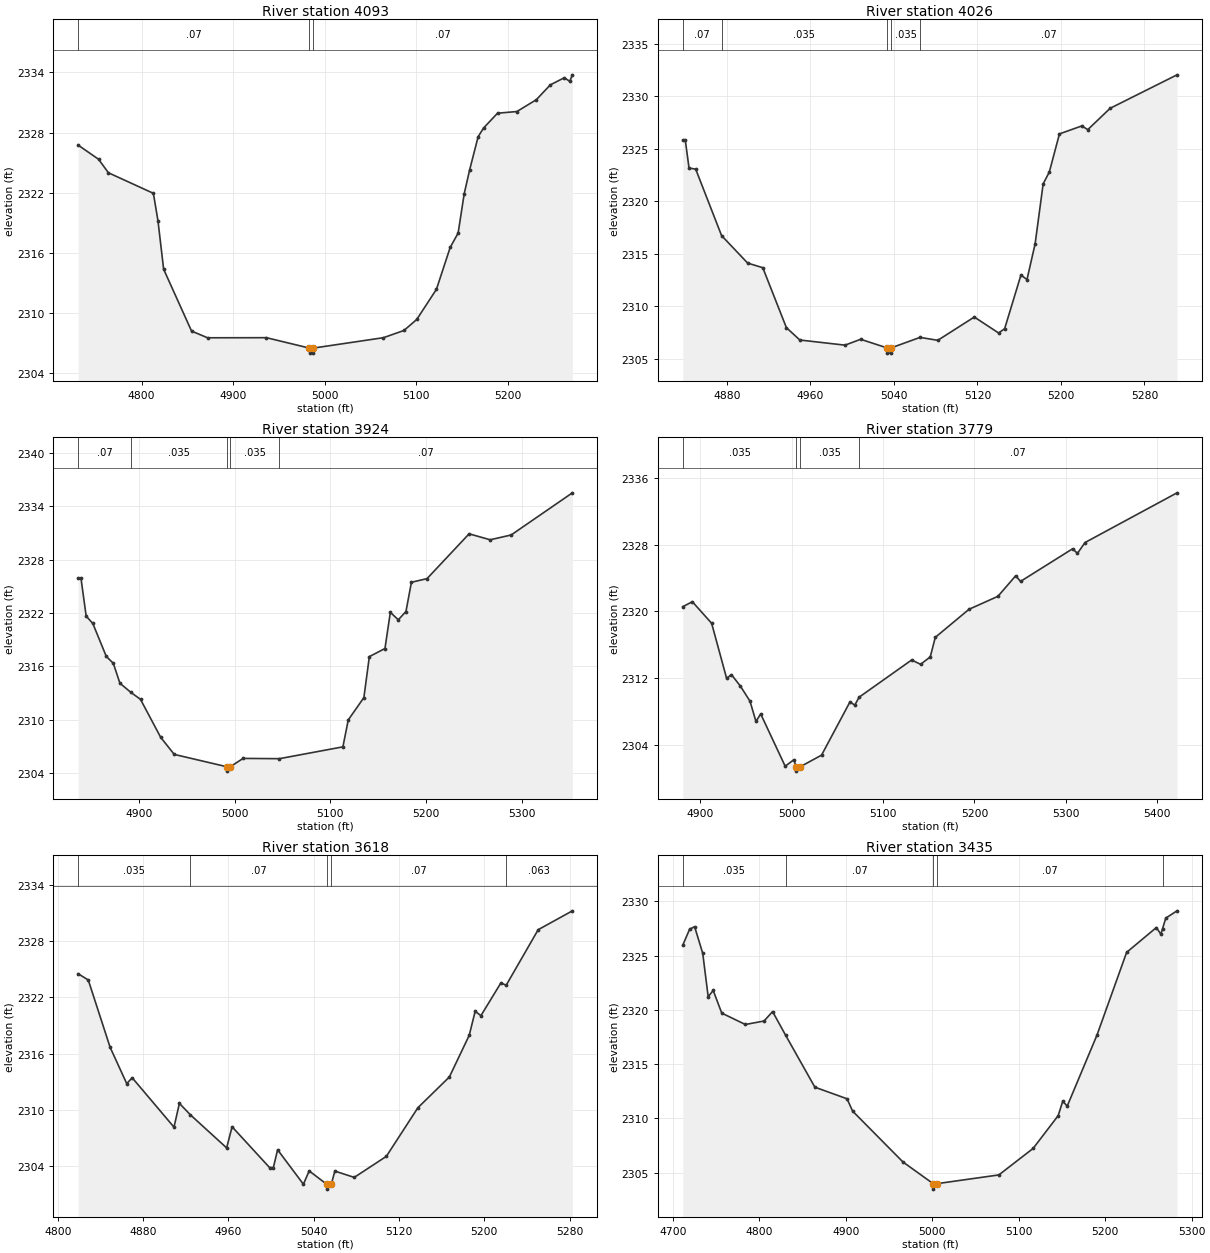
Type RM Length L Ch R = 1,4093,67,67,67
BEGIN DESCRIPTION:
Idlewild Creek Trib1 4419
END DESCRIPTION:
XS GIS Cut Line= 3
      1360574.97      6852280.01      1360528.13      6852014.71
      1360299.46      6851870.21
#Sta/Elev= 30
  4730.6 2326.75  4752.9 2325.34  4763.7 2323.99  4812.8 2321.94  4817.8 2319.21
  4824.0 2314.37  4854.5 2308.20  4872.0 2307.53  4936.3 2307.54  4983.3 2306.50
  4983.6 2306.00  4987.1 2306.00  4987.3 2306.50  5064.1 2307.54  5086.5 2308.26
  5100.5 2309.36  5122.0 2312.37  5137.0 2316.54  5145.7 2317.98  5152.3 2321.89
  5158.2 2324.26  5167.5 2327.58  5173.5 2328.46  5188.7 2329.93  5209.9 2330.10
  5231.1 2331.28  5246.4 2332.76  5261.7 2333.47  5267.6 2333.11  5270.5 2333.76
#Mann=3,-1,0
  4730.6    0.07       0  4983.3    0.07       0  4987.3    0.07       0
Bank Sta=4983.3,4987.3
Exp/Cntr=0.3,0.1

Type RM Length L Ch R = 1,4026,102,102,102
BEGIN DESCRIPTION:
Idlewild Creek Trib1 4423
END DESCRIPTION:
XS GIS Cut Line= 3
      1360703.81      6852067.45      1360575.31      6851968.14
      1360308.34      6851808.03
#Sta/Elev= 30
  4837.6 2325.85  4840.0 2325.85  4843.6 2323.18  4850.0 2323.07  4874.8 2316.74
  4899.8 2314.12  4914.3 2313.68  4936.9 2307.97  4949.8 2306.79  4993.1 2306.30
  5008.1 2306.86  5033.3 2306.04  5033.6 2305.54  5037.1 2305.54  5037.3 2306.04
  5065.0 2307.04  5082.0 2306.76  5117.0 2308.98  5140.3 2307.46  5146.1 2307.87
  5161.7 2312.98  5167.5 2312.55  5175.3 2315.96  5183.0 2321.67  5188.9 2322.80
  5198.6 2326.43  5220.0 2327.19  5225.8 2326.84  5247.2 2328.87  5311.3 2332.06
#Mann=5,-1,0
  4837.6    0.07       0  4874.8   0.035       0  5033.3   0.035       0
  5037.3   0.035       0  5065.0    0.07       0
Bank Sta=5033.3,5037.3
Exp/Cntr=0.3,0.1

Type RM Length L Ch R = 1,3924,145,145,145
BEGIN DESCRIPTION:
Idlewild Creek Trib1 7.1
END DESCRIPTION:
XS GIS Cut Line= 3
      1360727.39      6851997.39      1360615.78      6851878.32
      1360304.66      6851712.40
#Sta/Elev= 30
  4836.8 2325.91  4839.8 2325.91  4845.2 2321.66  4852.1 2320.84  4866.2 2317.13
  4873.5 2316.36  4880.4 2314.12  4891.7 2313.10  4901.9 2312.30  4922.9 2308.04
  4937.1 2306.11  4991.7 2304.73  4992.0 2304.23  4995.7 2304.73  5008.9 2305.66
  5046.8 2305.63  5113.1 2306.96  5118.7 2309.99  5135.0 2312.50  5140.7 2317.11
  5157.0 2318.02  5162.6 2322.09  5170.9 2321.25  5178.9 2322.18  5184.6 2325.47
  5200.9 2325.88  5244.8 2330.92  5266.8 2330.25  5288.7 2330.79  5352.6 2335.53
#Mann=5,-1,0
  4836.8    0.07       0  4891.7   0.035       0  4991.7   0.035       0
  4995.7   0.035       0  5046.8    0.07       0
Bank Sta=4991.7,4995.7
Exp/Cntr=0.3,0.1

Type RM Length L Ch R = 1,3779,161,161,161
BEGIN DESCRIPTION:
Idlewild Creek Trib1 7.0
END DESCRIPTION:
XS GIS Cut Line= 3
      1360755.01      6851888.02      1360718.33      6851774.61
      1360319.87      6851636.22
#Sta/Elev= 30
  4880.8 2320.56  4891.3 2321.16  4912.4 2318.57  4928.8 2311.96  4934.1 2312.40
  4943.9 2311.02  4954.4 2309.21  4960.9 2306.78  4966.1 2307.68  4992.9 2301.40
  5002.4 2302.18  5004.9 2301.31  5005.1 2300.81  5008.9 2301.31  5032.7 2302.73
  5063.8 2309.12  5069.1 2308.74  5073.8 2309.69  5131.3 2314.16  5141.1 2313.64
  5151.7 2314.53  5157.2 2316.88  5194.1 2320.25  5225.8 2321.81  5245.2 2324.28
  5250.5 2323.60  5307.5 2327.52  5312.8 2326.97  5321.1 2328.27  5421.8 2334.24
#Mann=4,-1,0
  4880.8   0.035       0  5004.9   0.035       0  5008.9   0.035       0
  5073.8    0.07       0
Bank Sta=5004.9,5008.9
Exp/Cntr=0.3,0.1

Type RM Length L Ch R = 1,3618,183,183,183
BEGIN DESCRIPTION:
Idlewild Creek Trib1 6.1
END DESCRIPTION:
XS GIS Cut Line= 3
      1360800.36      6851897.30      1360838.32      6851720.43
      1360944.08      6851458.26
#Sta/Elev= 30
  4819.1 2324.51  4828.6 2323.85  4849.1 2316.68  4864.7 2312.81  4869.8 2313.44
  4909.0 2308.18  4914.1 2310.71  4924.4 2309.49  4958.4 2305.97  4963.5 2308.22
  4998.7 2303.87  5002.2 2303.87  5006.2 2305.77  5030.4 2302.10  5035.8 2303.52
  5052.5 2302.08  5052.8 2301.58  5056.5 2302.08  5059.9 2303.50  5078.1 2302.83
  5108.2 2305.07  5137.8 2310.25  5167.3 2313.52  5185.9 2317.95  5191.5 2320.51
  5196.9 2320.05  5215.6 2323.53  5220.6 2323.29  5250.6 2329.20  5282.7 2331.21
#Mann=5,-1,0
  4819.1   0.035       0  4924.4    0.07       0  5052.5    0.07       0
  5056.5    0.07       0  5220.6   0.063       0
Bank Sta=5052.5,5056.5
Exp/Cntr=0.3,0.1

Type RM Length L Ch R = 1,3435,296,296,296
BEGIN DESCRIPTION:
Idlewild Creek Trib1 6.0
END DESCRIPTION:
XS GIS Cut Line= 3
      1360855.00      6852038.00      1360999.84      6851788.38
      1361075.12      6851515.47
#Sta/Elev= 30
  4711.4 2325.97  4719.3 2327.44  4725.1 2327.68  4734.5 2325.22  4740.8 2321.22
  4746.6 2321.80  4756.5 2319.71  4783.8 2318.66  4805.4 2318.98  4815.3 2319.85
  4830.5 2317.65  4864.2 2312.88  4901.4 2311.81  4907.9 2310.67  4966.0 2305.99
  5001.1 2303.98  5001.3 2303.48  5005.1 2303.98  5077.0 2304.79  5116.6 2307.23
  5145.6 2310.25  5150.9 2311.58  5156.1 2311.14  5190.5 2317.68  5224.8 2325.31
  5259.2 2327.60  5264.4 2326.98  5266.3 2327.48  5270.1 2328.47  5283.1 2329.14
#Mann=5,-1,0
  4711.4   0.035       0  4830.5    0.07       0  5001.1    0.07       0
  5005.1    0.07       0  5266.3   0.063       0
Bank Sta=5001.1,5005.1
Exp/Cntr=0.3,0.1

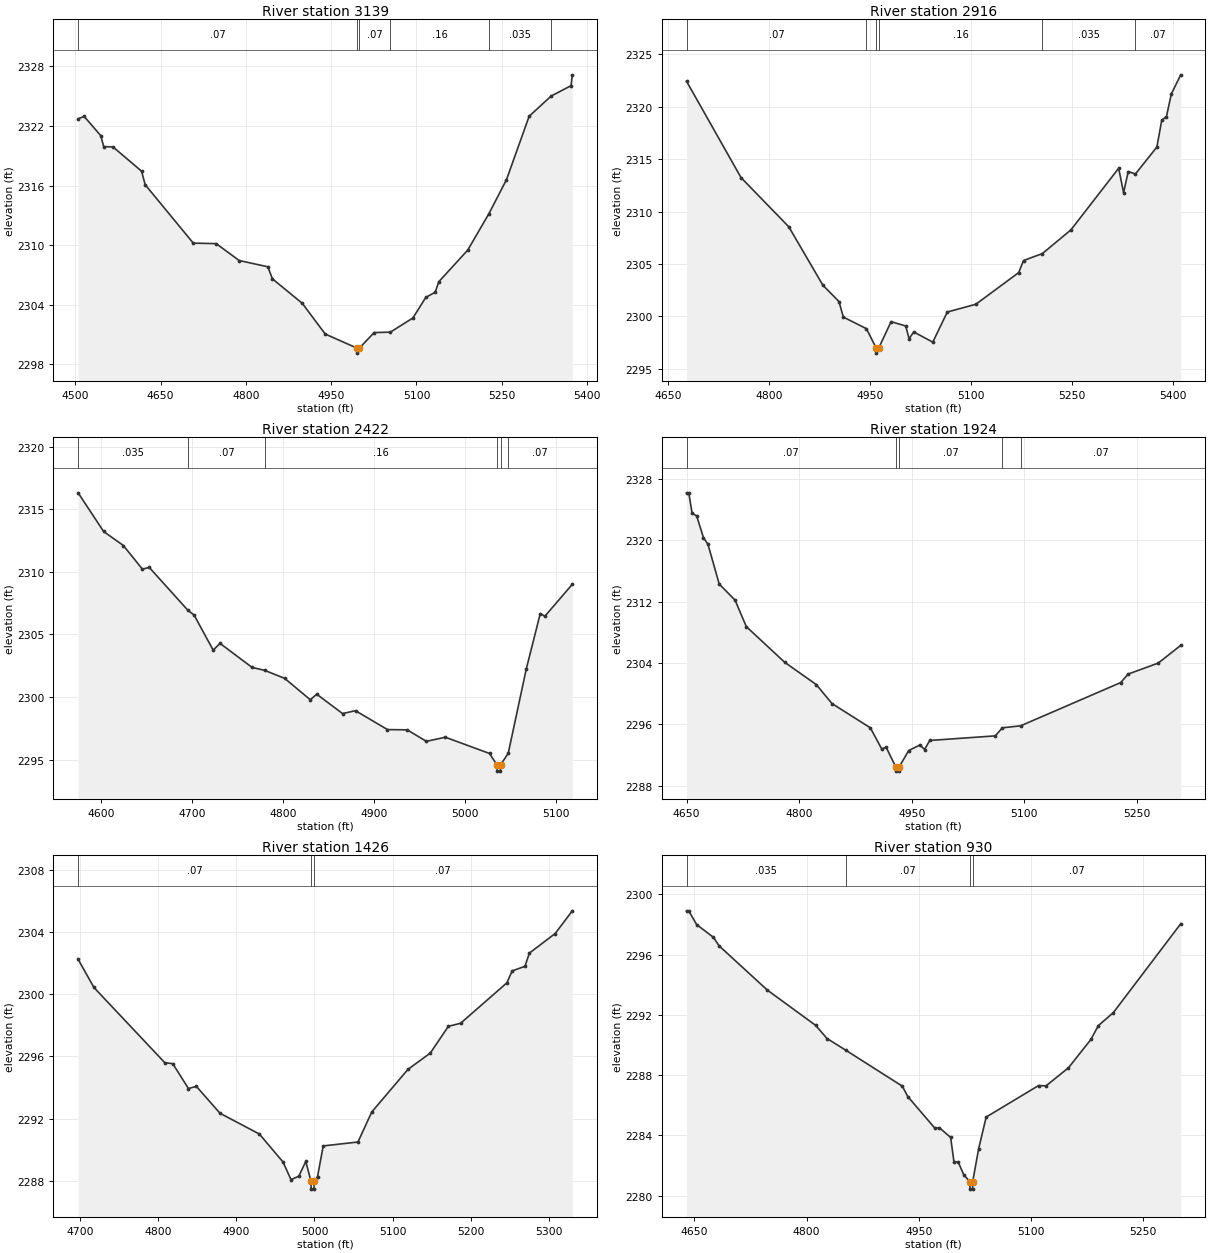
Type RM Length L Ch R = 1,3139,223,223,223
BEGIN DESCRIPTION:
Idlewild Creek Trib1 5.1
END DESCRIPTION:
XS GIS Cut Line= 3
      1361345.83      6852328.65      1361280.00      6851838.05
      1361119.41      6851500.28
#Sta/Elev= 30
  4505.0 2322.72  4515.7 2322.95  4544.9 2321.01  4550.0 2319.91  4566.2 2319.89
  4616.6 2317.44  4622.9 2316.08  4707.5 2310.20  4747.8 2310.15  4788.2 2308.45
  4838.6 2307.82  4846.6 2306.61  4899.2 2304.14  4939.5 2301.05  4995.5 2299.63
  4995.8 2299.13  4999.5 2299.63  5025.5 2301.20  5054.0 2301.24  5093.7 2302.67
  5116.4 2304.74  5132.9 2305.26  5139.1 2306.31  5190.1 2309.50  5227.0 2313.13
  5258.2 2316.58  5298.1 2322.97  5336.9 2325.01  5371.8 2326.05  5374.0 2327.14
#Mann=6,-1,0
  4505.0    0.07       0  4995.5    0.07       0  4999.5    0.07       0
  5054.0    0.16       0  5227.0   0.035       0  5336.9    0.07       0
Bank Sta=4995.5,4999.5
Exp/Cntr=0.3,0.1

Type RM Length L Ch R = 1,2916,494,494,494
BEGIN DESCRIPTION:
Idlewild Creek Trib1 5.0
END DESCRIPTION:
XS GIS Cut Line= 3
      1361804.96      6851837.99      1361486.78      6851787.88
      1361205.00      6851488.00
#Sta/Elev= 30
  4677.9 2322.43  4758.8 2313.24  4829.7 2308.55  4880.3 2302.98  4904.2 2301.42
  4910.7 2299.94  4945.0 2298.83  4959.3 2297.00  4959.6 2296.50  4963.3 2297.00
  4981.6 2299.50  5003.3 2299.09  5008.3 2297.87  5015.2 2298.52  5043.5 2297.55
  5065.0 2300.42  5107.4 2301.16  5171.0 2304.18  5178.2 2305.33  5206.3 2306.00
  5248.6 2308.26  5319.4 2314.13  5326.7 2311.80  5333.6 2313.82  5344.2 2313.58
  5376.1 2316.15  5383.4 2318.72  5390.3 2319.05  5397.6 2321.22  5411.5 2323.04
#Mann=6,-1,0
  4677.9    0.07       0  4945.0    0.16       0  4959.3    0.07       0
  4963.3    0.16       0  5206.3   0.035       0  5344.2    0.07       0
Bank Sta=4959.3,4963.3
Exp/Cntr=0.3,0.1

Type RM Length L Ch R = 1,2422,498,498,498
BEGIN DESCRIPTION:
Idlewild Creek Trib1 4.0
END DESCRIPTION:
XS GIS Cut Line= 3
      1361804.97      6851737.96      1361521.43      6851421.24
      1361405.03      6851438.00
#Sta/Elev= 30
  4574.9 2316.32  4602.9 2313.23  4624.6 2312.11  4645.5 2310.22  4653.0 2310.36
  4695.5 2306.93  4702.3 2306.55  4723.2 2303.75  4730.7 2304.29  4765.9 2302.37
  4779.9 2302.13  4801.8 2301.49  4829.9 2299.78  4836.9 2300.23  4865.3 2298.68
  4879.5 2298.91  4914.6 2297.40  4936.3 2297.38  4957.3 2296.46  4978.2 2296.79
  5026.7 2295.49  5034.8 2294.58  5035.1 2294.08  5038.6 2294.08  5038.8 2294.58
  5047.2 2295.50  5067.1 2302.26  5082.4 2306.67  5087.5 2306.46  5117.6 2309.01
#Mann=6,-1,0
  4574.9   0.035       0  4695.5    0.07       0  4779.9    0.16       0
  5034.8    0.07       0  5038.8    0.16       0  5047.2    0.07       0
Bank Sta=5034.8,5038.8
Exp/Cntr=0.3,0.1

Type RM Length L Ch R = 1,1924,498,498,498
BEGIN DESCRIPTION:
Idlewild Creek Trib1 3.0
END DESCRIPTION:
XS GIS Cut Line= 3
      1362055.02      6851238.01      1361763.47      6851044.19
      1361455.03      6851038.00
#Sta/Elev= 30
  4649.9 2326.19  4652.9 2326.19  4657.4 2323.51  4663.4 2323.19  4672.5 2320.34
  4678.5 2319.47  4693.5 2314.29  4714.6 2312.19  4729.6 2308.74  4780.7 2304.09
  4822.8 2301.18  4843.8 2298.70  4894.9 2295.54  4910.0 2292.79  4916.0 2292.99
  4929.0 2290.39  4929.3 2289.89  4932.8 2289.89  4933.0 2290.39  4946.0 2292.57
  4961.1 2293.31  4967.1 2292.71  4974.1 2293.89  5061.4 2294.49  5070.8 2295.54
  5095.2 2295.80  5228.5 2301.44  5238.5 2302.55  5278.5 2303.98  5308.5 2306.29
#Mann=5,-1,0
  4649.9    0.07       0  4929.0    0.07       0  4933.0    0.07       0
  5070.8    0.16       0  5095.2    0.07       0
Bank Sta=4929,4933
Exp/Cntr=0.3,0.1

Type RM Length L Ch R = 1,1426,496,496,496
BEGIN DESCRIPTION:
Idlewild Creek Trib1 2.0
END DESCRIPTION:
XS GIS Cut Line= 3
      1362005.05      6850638.01      1361705.19      6850602.12
      1361405.01      6850738.00
#Sta/Elev= 30
  4698.0 2302.24  4718.2 2300.43  4808.8 2295.59  4818.9 2295.53  4839.0 2293.93
  4849.1 2294.07  4879.3 2292.34  4929.7 2291.00  4959.9 2289.20  4970.0 2288.07
  4980.0 2288.29  4988.9 2289.24  4995.6 2287.96  4995.8 2287.46  4999.3 2287.46
  4999.6 2287.96  5003.9 2288.26  5011.2 2290.24  5055.6 2290.49  5073.2 2292.42
  5119.4 2295.16  5148.0 2296.21  5171.1 2297.93  5186.8 2298.13  5245.9 2300.73
  5252.7 2301.50  5269.0 2301.79  5274.6 2302.64  5307.6 2303.90  5329.5 2305.36
#Mann=3,-1,0
  4698.0    0.07       0  4995.6    0.07       0  4999.6    0.07       0
Bank Sta=4995.6,4999.6
Exp/Cntr=0.3,0.1

Type RM Length L Ch R = 1,930,455,455,455
BEGIN DESCRIPTION:
Idlewild Creek Trib1 1.0
END DESCRIPTION:
XS GIS Cut Line= 3
      1362104.97      6850337.98      1361804.92      6850137.97
      1361505.02      6850138.00
#Sta/Elev= 30
  4639.4 2298.90  4642.4 2298.90  4652.9 2297.99  4675.4 2297.14  4682.9 2296.58
  4747.5 2293.64  4812.1 2291.30  4827.2 2290.43  4852.1 2289.66  4927.8 2287.27
  4935.3 2286.57  4971.4 2284.48  4977.4 2284.51  4992.4 2283.87  4996.9 2282.24
  5002.5 2282.24  5009.9 2281.40  5017.9 2280.94  5018.2 2280.44  5021.7 2280.44
  5021.9 2280.94  5029.9 2283.13  5039.9 2285.22  5109.9 2287.31  5119.9 2287.29
  5149.9 2288.49  5179.9 2290.37  5189.9 2291.29  5209.9 2292.15  5299.9 2298.04
#Mann=4,-1,0
  4639.4   0.035       0  4852.1    0.07       0  5017.9    0.07       0
  5021.9    0.07       0
Bank Sta=5017.9,5021.9
Exp/Cntr=0.3,0.1

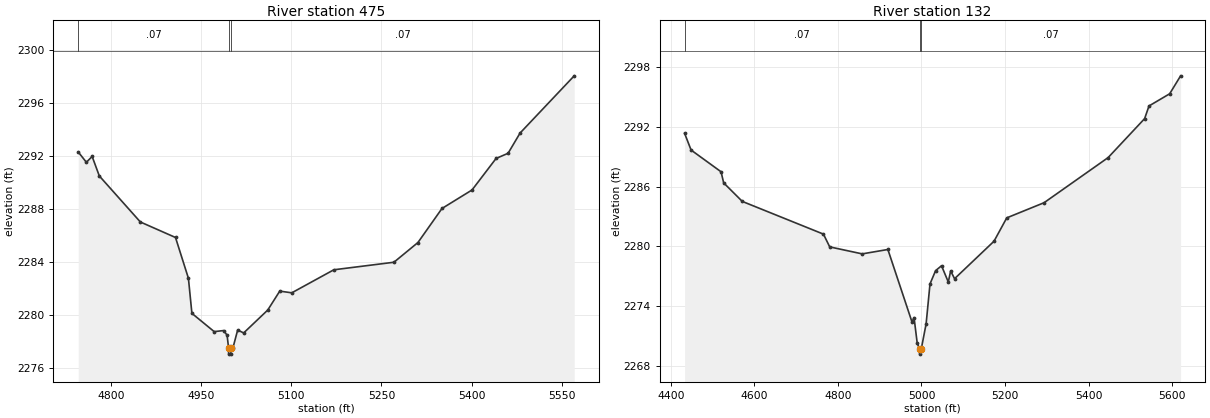
Type RM Length L Ch R = 1,475,343,343,343
BEGIN DESCRIPTION:
Idlewild Creek Trib1 0.1
END DESCRIPTION:
XS GIS Cut Line= 3
      1362204.98      6850037.97      1362075.53      6849818.27
      1361504.98      6849838.00
#Sta/Elev= 30
  4745.0 2292.32  4758.6 2291.54  4768.2 2291.98  4780.1 2290.51  4848.5 2287.03
  4907.0 2285.86  4928.5 2282.78  4934.3 2280.13  4971.4 2278.75  4987.1 2278.83
  4992.9 2278.48  4995.3 2277.55  4995.5 2277.05  4999.0 2277.05  4999.3 2277.55
  5002.8 2277.55  5010.5 2278.87  5020.5 2278.65  5060.6 2280.38  5080.6 2281.81
  5100.6 2281.68  5170.6 2283.42  5270.7 2283.99  5310.7 2285.48  5350.7 2288.05
  5400.8 2289.45  5440.8 2291.83  5460.8 2292.22  5480.8 2293.75  5570.9 2298.07
#Mann=3,-1,0
  4745.0    0.07       0  4995.3    0.07       0  4999.3    0.07       0
Bank Sta=4995.3,4999.3
Exp/Cntr=0.3,0.1

Type RM Length L Ch R = 1,132,0,0,0
BEGIN DESCRIPTION:
Idlewild Creek Trib1 4469
END DESCRIPTION:
XS GIS Cut Line= 4
      1362429.07      6849875.25      1362180.38      6849510.68
      1362054.72      6849501.52      1361508.64      6849796.37
#Sta/Elev= 30
  4432.7 2291.33  4448.2 2289.66  4520.0 2287.48  4526.2 2286.37  4570.8 2284.51
  4765.2 2281.23  4780.2 2279.95  4858.0 2279.25  4919.5 2279.69  4977.2 2272.43
  4982.2 2272.86  4989.7 2270.32  4995.4 2269.70  4995.6 2269.20  4999.4 2269.70
  5011.1 2272.24  5020.4 2276.24  5033.8 2277.57  5048.0 2278.06  5064.2 2276.43
  5069.9 2277.54  5079.2 2276.76  5173.7 2280.52  5204.2 2282.86  5293.6 2284.38
  5446.9 2288.90  5534.4 2292.81  5544.9 2294.08  5594.4 2295.30  5620.6 2297.10
#Mann=3,-1,0
  4432.7    0.07       0  4995.4    0.07       0  4999.4    0.07       0
Bank Sta=4995.4,4999.4
Exp/Cntr=0.3,0.1

Chan Stop Cuts=-1