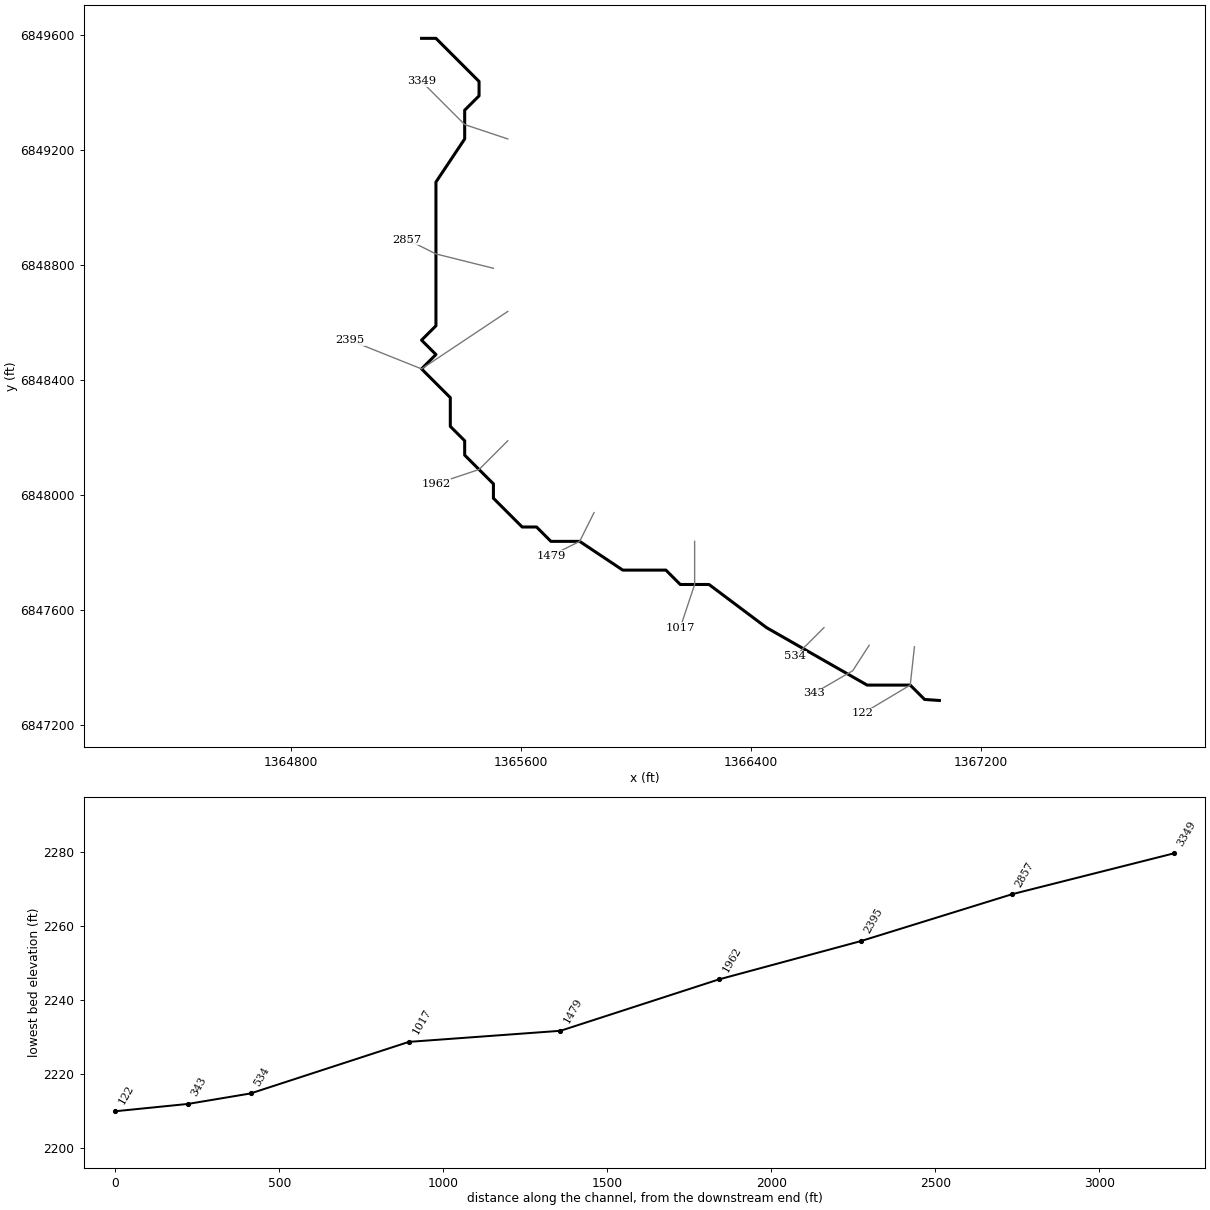
--- Idlewild Creek Trib2.prj (project) ---

Proj Title=Idlewild Creek Trib2 Base Level Engineering
Current Plan=p01
Default Exp/Contr=0.3,0.1
English Units
Geom File=g01
Flow File=f01
Plan File=p01
Y Axis Title=Elevation
X Axis Title(PF)=Main Channel Distance
X Axis Title(XS)=Station
BEGIN DESCRIPTION:
Idlewild Creek Trib2
END DESCRIPTION:
DSS Export Rating Curves= 0
DSS Export Rating Curve Sorted= 0
DSS Export Volume Flow Curves= 0
DXF OffsetX= 0
DXF OffsetY= 0
DXF ScaleX= 1
DXF ScaleY= 10

--- Idlewild Creek Trib2.p01 (plan) ---

Plan Title=Multiple Run
Short Identifier=Multiple
Geom File=g01
Flow File=f01
Subcritical Flow
K Sum by GR= 0
Std Step Tol= 0.01
Critical Tol= 0.01
Num of Std Step Trials= 20
Max Error Tol= 0.3
Flow Tol Ratio= 0.001
Split Flow NTrial= 30
Split Flow Tol= 0.02
Split Flow Ratio= 0.02
Log Output Level= 0
Friction Slope Method= 1
Unsteady Friction Slope Method= 2
Unsteady Bridges Friction Slope Method= 1
Parabolic Critical Depth
Global Vel Dist=  1 , 1 , 1
Global Log Level= 0
CheckData=True
Encroach Param= -1, 0, 0, 0
BEGIN DESCRIPTION:
Multiple Run
END DESCRIPTION:

--- Idlewild Creek Trib2.f01 (steady flow) ---

Flow Title=Multiple
Program Version=4.10
Number of Profiles= 7
Profile Names=10-year,25-year,50-year,1pct_min,100-year,1pct_plu,500-year
River Rch & RM=Idlewild Creek T,Reach-1         ,3349
      71      93     111      66     131     262     187
River Rch & RM=Idlewild Creek T,Reach-1         ,534
     123     170     209     128     255     510     387
Boundary for River Rch & Prof#=Idlewild Creek T,Reach-1         , 1
Up Type= 0
Dn Type= 3
Dn Slope=0.009
Boundary for River Rch & Prof#=Idlewild Creek T,Reach-1         , 2
Up Type= 0
Dn Type= 3
Dn Slope=0.009
Boundary for River Rch & Prof#=Idlewild Creek T,Reach-1         , 3
Up Type= 0
Dn Type= 3
Dn Slope=0.009
Boundary for River Rch & Prof#=Idlewild Creek T,Reach-1         , 4
Up Type= 0
Dn Type= 3
Dn Slope=0.009
Boundary for River Rch & Prof#=Idlewild Creek T,Reach-1         , 5
Up Type= 0
Dn Type= 3
Dn Slope=0.009
Boundary for River Rch & Prof#=Idlewild Creek T,Reach-1         , 6
Up Type= 0
Dn Type= 3
Dn Slope=0.009
Boundary for River Rch & Prof#=Idlewild Creek T,Reach-1         , 7
Up Type= 0
Dn Type= 3
Dn Slope=0.009
DSS Import GetInterval= 0
DSS Import GetPeak= 0
DSS Import FillOption= 0

--- Idlewild Creek Trib2.g01 (geometry) ---

Geom Title=Existing Conditions
Program Version=4.10

River Reach=Idlewild Creek T,Reach-1
Reach XY= 30
        1365255.        6849588.        1365305.        6849588.
        1365455.        6849438.        1365455.        6849388.
        1365405.        6849338.        1365405.        6849238.
        1365305.        6849088.        1365305.        6848588.
        1365255.        6848538.        1365305.        6848488.
        1365255.        6848438.        1365355.        6848338.
        1365355.        6848238.        1365405.        6848188.
        1365405.        6848138.        1365505.        6848038.
        1365505.        6847988.        1365605.        6847888.
        1365655.        6847888.        1365705.        6847838.
        1365805.        6847838.        1365955.        6847738.
        1366105.        6847738.        1366155.        6847688.
        1366255.        6847688.        1366455.        6847538.
        1366805.        6847338.        1366955.        6847338.
        1367005.        6847288.      1367056.46      6847284.48

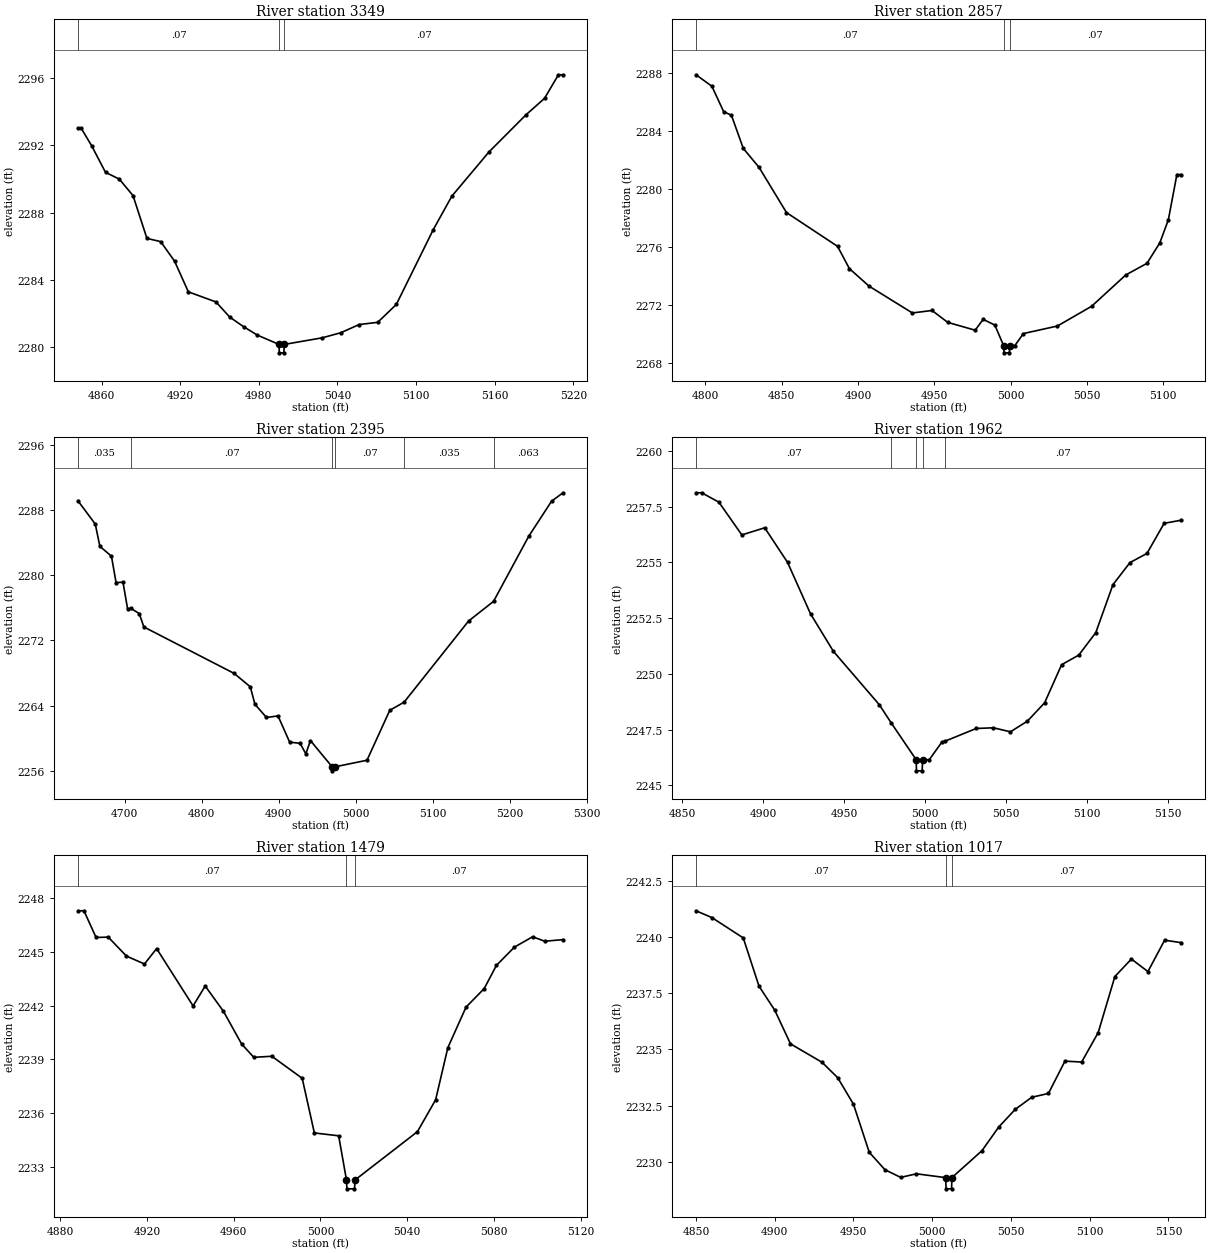
Type RM Length L Ch R = 1 ,3349    ,492,492,492
BEGIN DESCRIPTION:
Idlewild Creek Trib2 7.0
END DESCRIPTION:
XS GIS Cut Line= 3
      1365554.99        6849238.        1365405.        6849288.
      1365255.02      6849437.98
#Sta/Elev= 30
  4841.9    2293  4844.5    2293  4852.4 2291.97    4863 2290.39  4873.5 2289.99
    4884 2289.01  4894.6 2286.47  4905.1 2286.28  4915.7 2285.12  4926.2  2283.3
  4947.3  2282.7  4957.8  2281.8  4968.4 2281.23  4978.9 2280.73  4995.4 2280.18
  4995.6 2279.68  4999.1 2279.68  4999.4 2280.18  5028.3 2280.57  5042.4 2280.87
  5056.6 2281.36  5070.7 2281.49  5084.9 2282.55  5113.1 2286.99  5127.3 2288.98
  5155.6  2291.6  5183.8  2293.8    5198 2294.78  5208.6 2296.18  5212.1 2296.18
#Mann= 3 ,-1 , 0
  4841.9     .07       0  4995.4     .07       0  4999.4     .07       0
Bank Sta=4995.4,4999.4
XS Rating Curve= 0 ,0
Exp/Cntr=0.3,0.1

Type RM Length L Ch R = 1 ,2857    ,462,462,462
BEGIN DESCRIPTION:
Idlewild Creek Trib2 6.0
END DESCRIPTION:
XS GIS Cut Line= 3
      1365505.04      6848787.99        1365305.        6848838.
        1365205.        6848888.
#Sta/Elev= 30
  4793.8 2287.85  4804.2 2287.06  4811.9 2285.31    4817 2285.06  4824.8 2282.77
  4835.1 2281.47  4853.1 2278.35  4886.6 2276.02  4894.3 2274.49  4907.2 2273.28
  4935.6 2271.43  4948.5  2271.6  4958.8 2270.78  4976.8 2270.24    4982 2270.99
  4989.7 2270.59  4995.4 2269.18  4995.7 2268.68  4999.2 2268.68  4999.4 2269.18
  5002.8 2269.18  5008.4 2270.01  5030.7 2270.53  5053.1 2271.89  5075.5 2274.05
  5089.4 2274.85  5097.8 2276.26  5103.4 2277.85    5109 2280.97  5111.8 2280.97
#Mann= 3 ,-1 , 0
  4793.8     .07       0  4995.4     .07       0  4999.4     .07       0
Bank Sta=4995.4,4999.4
XS Rating Curve= 0 ,0
Exp/Cntr=0.3,0.1

Type RM Length L Ch R = 1 ,2395    ,433,433,433
BEGIN DESCRIPTION:
Idlewild Creek Trib2 5.0
END DESCRIPTION:
XS GIS Cut Line= 3
      1365555.04      6848638.02        1365255.        6848438.
      1365004.96      6848538.02
#Sta/Elev= 30
  4639.4 2289.16    4662 2286.29    4668 2283.55    4683 2282.35    4689 2279.11
    4698 2279.15    4704 2275.87  4708.3 2275.93  4719.1 2275.31  4725.1 2273.66
  4842.3 2267.96  4863.3 2266.31  4869.3 2264.17  4884.3 2262.55  4899.3 2262.74
  4914.4 2259.52  4927.9 2259.38  4935.4 2258.09  4941.4 2259.71  4969.5  2256.5
  4969.7    2256  4973.5  2256.5  5014.8  2257.3  5044.4 2263.43  5062.9 2264.42
  5146.7 2274.39  5179.1  2276.8  5224.8 2284.79  5254.4 2289.09  5269.3 2290.13
#Mann= 6 ,-1 , 0
  4639.4    .035       0  4708.3     .07       0  4969.5     .07       0
  4973.5     .07       0  5062.9    .035       0  5179.1    .063       0
Bank Sta=4969.5,4973.5
XS Rating Curve= 0 ,0
Exp/Cntr=0.3,0.1

Type RM Length L Ch R = 1 ,1962    ,483,483,483
BEGIN DESCRIPTION:
Idlewild Creek Trib2 4.0
END DESCRIPTION:
XS GIS Cut Line= 3
      1365554.98      6848187.98        1365455.        6848088.
      1365305.01        6848038.
#Sta/Elev= 30
  4858.6 2258.12  4862.1 2258.12  4872.7  2257.7  4886.9 2256.23    4901 2256.55
  4915.1    2255  4929.3 2252.69  4943.4 2251.01  4971.7 2248.62  4979.1  2247.8
  4994.5 2246.15  4994.7 2245.65  4998.2 2245.65  4998.5 2246.15  5002.6 2246.15
  5010.5 2246.95  5012.3 2246.98  5031.6 2247.55  5042.2 2247.58  5052.7  2247.4
  5063.2 2247.88  5073.8  2248.7  5084.3 2250.41  5094.9 2250.84  5105.4 2251.85
    5116    2254  5126.5 2254.99    5137  2255.4  5147.6 2256.75  5158.1 2256.89
#Mann= 5 ,-1 , 0
  4858.6     .07       0  4979.1     .16       0  4994.5     .07       0
  4998.5     .16       0  5012.3     .07       0
Bank Sta=4994.5,4998.5
XS Rating Curve= 0 ,0
Exp/Cntr=0.3,0.1

Type RM Length L Ch R = 1 ,1479    ,462,462,462
BEGIN DESCRIPTION:
Idlewild Creek Trib2 3.0
END DESCRIPTION:
XS GIS Cut Line= 3
        1365855.        6847938.        1365805.        6847838.
        1365705.        6847788.
#Sta/Elev= 30
  4888.2  2247.3    4891  2247.3  4896.6 2245.81  4902.2 2245.83  4910.6 2244.77
  4918.9 2244.33  4924.5 2245.19  4941.3 2241.99  4946.9  2243.1  4955.3 2241.69
  4963.7 2239.86  4969.3 2239.12  4977.6 2239.18  4991.6 2237.95  4997.2  2234.9
  5008.4 2234.74    5012 2232.28  5012.2 2231.78  5015.7 2231.78    5016 2232.28
  5044.7 2234.97  5053.1 2236.75  5058.7 2239.65  5067.1 2241.92  5075.5 2242.96
  5081.1 2244.25  5089.4 2245.27  5097.8 2245.85  5103.4  2245.6  5111.8 2245.69
#Mann= 3 ,-1 , 0
  4888.2     .07       0    5012     .07       0    5016     .07       0
Bank Sta=5012,5016
XS Rating Curve= 0 ,0
Exp/Cntr=0.3,0.1

Type RM Length L Ch R = 1 ,1017    ,483,483,483
BEGIN DESCRIPTION:
Idlewild Creek Trib2 2.0
END DESCRIPTION:
XS GIS Cut Line= 3
        1366205.        6847838.        1366205.        6847688.
        1366155.      6847538.01
#Sta/Elev= 30
    4850 2241.18    4860 2240.88    4880 2239.97    4890 2237.82    4900 2236.75
    4910 2235.25    4930 2234.43    4940 2233.74    4950 2232.56    4960 2230.42
    4970 2229.64    4980  2229.3    4990 2229.46  5008.5 2229.29  5008.8 2228.79
  5012.3 2228.79  5012.5 2229.29  5031.6 2230.49  5042.2 2231.54  5052.7 2232.33
  5063.2 2232.87  5073.8 2233.04  5084.3 2234.48  5094.9 2234.44  5105.4 2235.75
    5116 2238.25  5126.5 2239.03    5137 2238.47  5147.6 2239.87  5158.1 2239.76
#Mann= 3 ,-1 , 0
    4850     .07       0  5008.5     .07       0  5012.5     .07       0
Bank Sta=5008.5,5012.5
XS Rating Curve= 0 ,0
Exp/Cntr=0.3,0.1

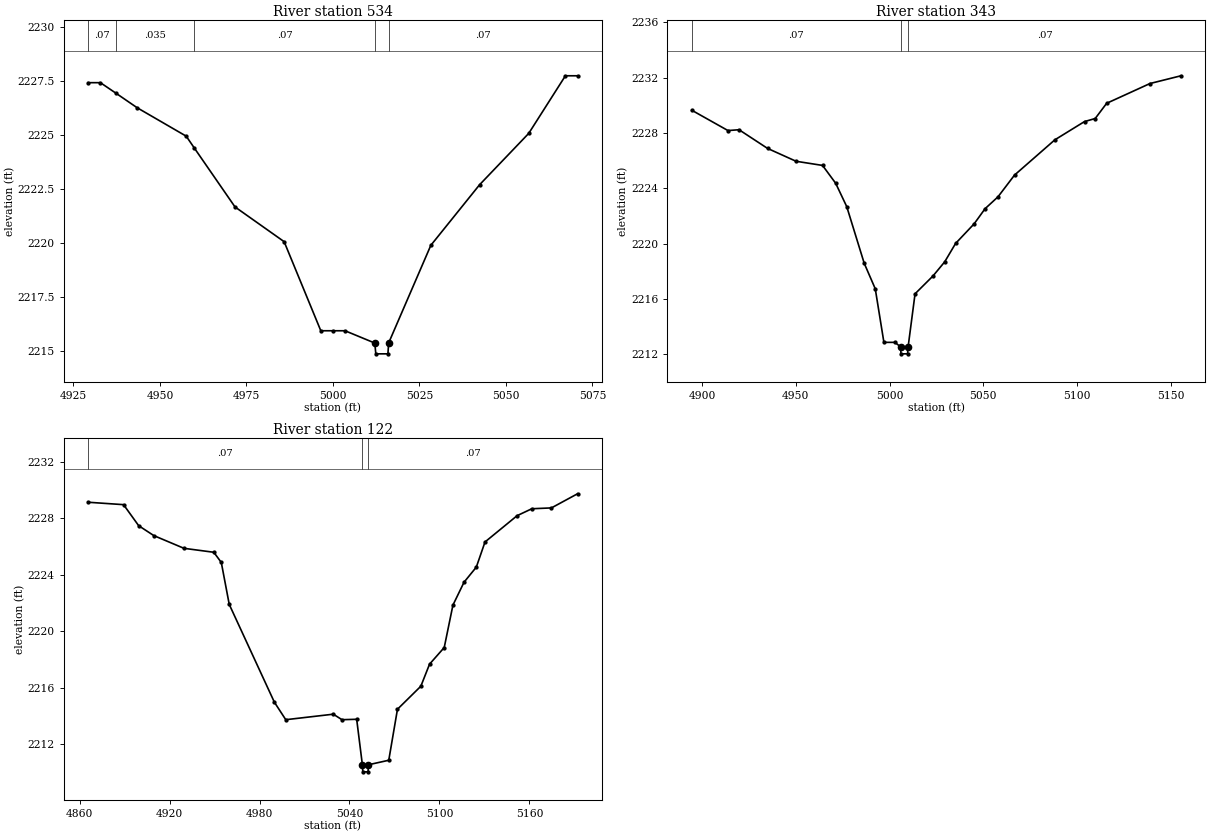
Type RM Length L Ch R = 1 ,534     ,191,191,191
BEGIN DESCRIPTION:
Idlewild Creek Trib2 1.0
END DESCRIPTION:
XS GIS Cut Line= 3
      1366654.99      6847537.99        1366605.        6847488.
      1366555.01      6847438.01
#Sta/Elev= 20
  4929.3 2227.43  4932.8 2227.43  4937.4 2226.93  4943.4 2226.27  4957.6 2224.95
  4959.9 2224.41  4971.7 2221.67  4985.9 2220.06  4996.5 2215.93    5000 2215.93
  5003.5 2215.93  5012.1 2215.36  5012.4 2214.86  5015.9 2214.86  5016.1 2215.36
  5028.3 2219.89  5042.4  2222.7  5056.6 2225.08  5067.2 2227.75  5070.7 2227.75
#Mann= 5 ,-1 , 0
  4929.3     .07       0  4937.4    .035       0  4959.9     .07       0
  5012.1     .07       0  5016.1     .07       0
Bank Sta=5012.1,5016.1
XS Rating Curve= 0 ,0
Exp/Cntr=0.3,0.1

Type RM Length L Ch R = 1 ,343     ,221,221,221
BEGIN DESCRIPTION:
Idlewild Creek Trib2 4470
END DESCRIPTION:
XS GIS Cut Line= 3
      1366812.14      6847476.57        1366755.        6847388.
      1366620.75      6847309.92
#Sta/Elev= 30
  4894.6 2229.64  4913.9 2228.17  4919.8 2228.23    4935 2226.88  4950.2 2225.95
  4964.3 2225.65  4971.3 2224.36  4977.2 2222.67  4986.5 2218.58  4992.4 2216.73
    4997 2212.86  5002.9 2212.86  5005.9 2212.53  5006.1 2212.03  5009.6 2212.03
  5009.9 2212.53  5013.6 2216.37  5023.1 2217.65  5029.4 2218.68  5035.2 2220.01
  5045.1 2221.43  5050.9 2222.52  5057.8 2223.38  5066.6 2224.95  5088.1  2227.5
  5103.9 2228.82  5109.6 2229.04  5115.7 2230.14  5138.8 2231.57  5155.3 2232.13
#Mann= 3 ,-1 , 0
  4894.6     .07       0  5005.9     .07       0  5009.9     .07       0
Bank Sta=5005.9,5009.9
XS Rating Curve= 0 ,0
Exp/Cntr=0.3,0.1

Type RM Length L Ch R = 1 ,122     ,0,0,0
BEGIN DESCRIPTION:
Idlewild Creek Trib2 4471
END DESCRIPTION:
XS GIS Cut Line= 3
       1366969.7      6847471.39        1366955.        6847338.
      1366790.01       6847239.6
#Sta/Elev= 30
  4865.8 2229.14  4889.3 2228.97  4899.4 2227.48  4909.5 2226.78  4929.6 2225.88
  4949.5  2225.6  4954.5 2224.88  4959.8 2221.91  4989.9 2214.99  4997.5 2213.75
  5029.2 2214.14    5035 2213.75  5044.8 2213.78  5048.6 2210.56  5048.9 2210.06
  5052.4 2210.06  5052.6 2210.56  5066.2 2210.88    5072 2214.49  5087.6 2216.12
  5093.4 2217.68  5103.2 2218.86    5109 2221.86  5116.4 2223.48  5124.6 2224.55
  5130.4 2226.33  5151.8 2228.19  5161.6 2228.68  5174.7 2228.74  5192.1 2229.74
#Mann= 3 ,-1 , 0
  4865.8     .07       0  5048.6     .07       0  5052.6     .07       0
Bank Sta=5048.6,5052.6
XS Rating Curve= 0 ,0
Exp/Cntr=0.3,0.1

Chan Stop Cuts=-1
Use User Specified Reach Order=0
Composite Channel Slope=5