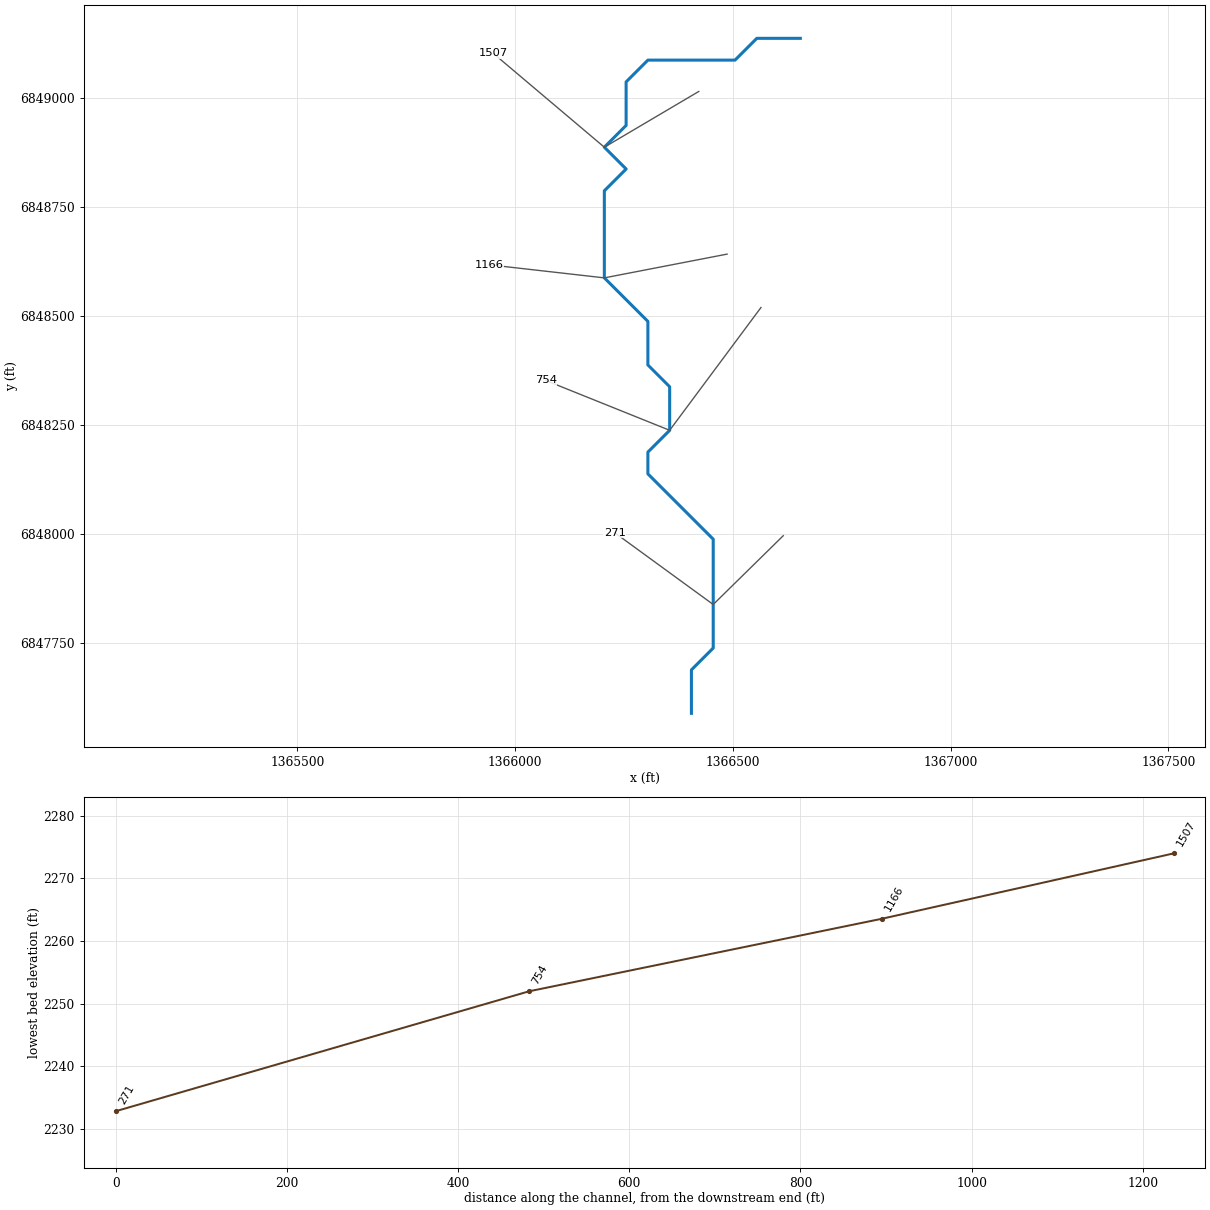
--- Idlewild Creek Trib2T.prj (project) ---

Proj Title=Idlewild Creek Trib2T Base Level Engineering
Current Plan=p01
Default Exp/Contr=0.3,0.1
English Units
Geom File=g01
Flow File=f01
Plan File=p01
BEGIN DESCRIPTION:
Idlewild Creek Trib2T
END DESCRIPTION:

--- Idlewild Creek Trib2T.p01 (plan) ---

Plan Title=Multiple Run
Short Identifier=Multiple
Geom File=g01
Flow File=f01
Subcritical Flow
K Sum by GR= 0
Std Step Tol= 0.01
Critical Tol= 0.01
Num of Std Step Trials= 20
Max Error Tol= 0.3
Flow Tol Ratio= 0.001
Split Flow NTrial= 30
Split Flow Tol= 0.02
Split Flow Ratio= 0.02
Log Output Level= 0
Friction Slope Method= 1
Unsteady Friction Slope Method= 2
Unsteady Bridges Friction Slope Method= 1
Parabolic Critical Depth
Global Vel Dist=  1 , 1 , 1
Global Log Level= 0
CheckData=True
Encroach Param= -1, 0, 0, 0
BEGIN DESCRIPTION:
Multiple Run
END DESCRIPTION:

--- Idlewild Creek Trib2T.f01 (steady flow) ---

Flow Title=Multiple
Number of Profiles=7
Profile Names=10-year,25-year,50-year,1pct_min,100-year,1pct_plu,500-year
River Rch & RM= Idlewild Creek T,Reach-1,1507
      32      40      46      26      52     105      69
Boundary for River Rch & Prof#=Idlewild Creek T,Reach-1,1
Up Type=0
Dn Type=3
Dn Slope=0.005
Boundary for River Rch & Prof#=Idlewild Creek T,Reach-1,2
Up Type=0
Dn Type=3
Dn Slope=0.005
Boundary for River Rch & Prof#=Idlewild Creek T,Reach-1,3
Up Type=0
Dn Type=3
Dn Slope=0.005
Boundary for River Rch & Prof#=Idlewild Creek T,Reach-1,4
Up Type=0
Dn Type=3
Dn Slope=0.005
Boundary for River Rch & Prof#=Idlewild Creek T,Reach-1,5
Up Type=0
Dn Type=3
Dn Slope=0.005
Boundary for River Rch & Prof#=Idlewild Creek T,Reach-1,6
Up Type=0
Dn Type=3
Dn Slope=0.005
Boundary for River Rch & Prof#=Idlewild Creek T,Reach-1,7
Up Type=0
Dn Type=3
Dn Slope=0.005

--- Idlewild Creek Trib2T.g01 (geometry) ---

Geom Title=Existing Conditions

River Reach=Idlewild Creek T,Reach-1
Reach XY= 20
      1366655.00      6849138.00      1366555.00      6849138.00
      1366505.00      6849088.00      1366305.00      6849088.00
      1366255.00      6849038.00      1366255.00      6848938.00
      1366205.00      6848888.00      1366255.00      6848838.00
      1366205.00      6848788.00      1366205.00      6848588.00
      1366305.00      6848488.00      1366305.00      6848388.00
      1366355.00      6848338.00      1366355.00      6848238.00
      1366305.00      6848188.00      1366305.00      6848138.00
      1366455.00      6847988.00      1366455.00      6847738.00
      1366405.00      6847688.00      1366405.00      6847588.00

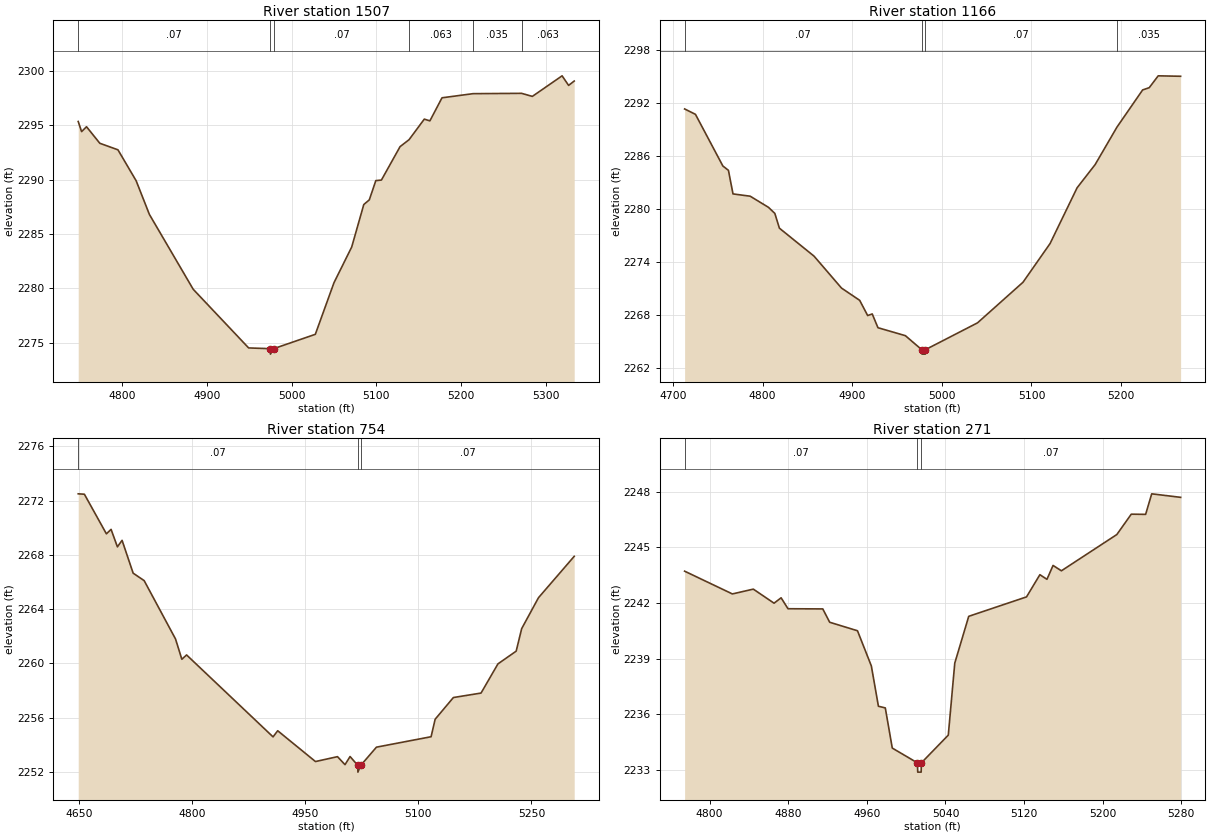
Type RM Length L Ch R = 1,1507,341,341,341
BEGIN DESCRIPTION:
Idlewild Creek Trib2T 4.0
END DESCRIPTION:
XS GIS Cut Line= 3
      1366421.84      6849016.01      1366205.00      6848888.00
      1365950.27      6849103.25
#Sta/Elev= 30
  4748.2 2295.34  4752.2 2294.41  4758.0 2294.86  4773.7 2293.34  4795.1 2292.74
  4816.6 2289.89  4832.2 2286.80  4883.9 2279.92  4949.3 2274.53  4974.8 2274.46
  4975.0 2273.96  4978.8 2274.46  5028.0 2275.78  5050.0 2280.52  5070.9 2283.80
  5085.2 2287.71  5091.7 2288.14  5099.4 2289.91  5106.0 2289.96  5128.0 2293.03
  5138.6 2293.67  5156.6 2295.56  5163.2 2295.40  5177.5 2297.52  5214.1 2297.90
  5271.4 2297.93  5284.1 2297.65  5319.2 2299.54  5326.9 2298.66  5333.5 2299.06
#Mann=6,-1,0
  4748.2    0.07       0  4974.8    0.07       0  4978.8    0.07       0
  5138.6   0.063       0  5214.1   0.035       0  5271.4   0.063       0
Bank Sta=4974.8,4978.8
Exp/Cntr=0.3,0.1

Type RM Length L Ch R = 1,1166,412,412,412
BEGIN DESCRIPTION:
Idlewild Creek Trib2T 3.0
END DESCRIPTION:
XS GIS Cut Line= 3
      1366486.87      6848642.52      1366205.00      6848588.00
      1365940.20      6848618.05
#Sta/Elev= 30
  4712.9 2291.30  4725.0 2290.69  4755.6 2284.84  4761.8 2284.35  4766.9 2281.68
  4786.1 2281.42  4806.5 2280.16  4813.6 2279.47  4818.7 2277.80  4857.4 2274.63
  4888.0 2271.02  4908.3 2269.63  4917.2 2267.91  4922.3 2268.09  4928.7 2266.53
  4959.3 2265.63  4977.6 2264.04  4977.9 2263.54  4981.4 2263.54  4981.6 2264.04
  5039.8 2267.08  5090.6 2271.68  5120.8 2276.06  5151.0 2282.38  5171.1 2285.00
  5195.5 2289.25  5224.1 2293.45  5231.5 2293.71  5241.5 2295.05  5266.5 2295.00
#Mann=4,-1,0
  4712.9    0.07       0  4977.6    0.07       0  4981.6    0.07       0
  5195.5   0.035       0
Bank Sta=4977.6,4981.6
Exp/Cntr=0.3,0.1

Type RM Length L Ch R = 1,754,483,483,483
BEGIN DESCRIPTION:
Idlewild Creek Trib2T 2.0
END DESCRIPTION:
XS GIS Cut Line= 3
      1366564.64      6848519.89      1366355.00      6848238.00
      1366070.34      6848352.43
#Sta/Elev= 30
  4648.7 2272.50  4656.9 2272.47  4686.1 2269.55  4692.3 2269.88  4700.7 2268.59
  4706.9 2269.07  4721.6 2266.65  4736.2 2266.10  4777.8 2261.80  4786.2 2260.30
  4792.5 2260.62  4907.2 2254.58  4913.4 2255.03  4963.5 2252.76  4992.7 2253.12
  5002.7 2252.53  5009.4 2253.13  5019.6 2252.48  5019.8 2251.98  5023.6 2252.48
  5044.4 2253.82  5116.9 2254.59  5122.3 2255.88  5146.5 2257.48  5183.2 2257.81
  5205.6 2259.96  5229.8 2260.90  5237.1 2262.56  5259.4 2264.84  5306.8 2267.89
#Mann=3,-1,0
  4648.7    0.07       0  5019.6    0.07       0  5023.6    0.07       0
Bank Sta=5019.6,5023.6
Exp/Cntr=0.3,0.1

Type RM Length L Ch R = 1,271,0,0,0
BEGIN DESCRIPTION:
Idlewild Creek Trib2T 1.0
END DESCRIPTION:
XS GIS Cut Line= 3
      1366615.81      6847995.94      1366455.00      6847838.00
      1366229.27      6848002.48
#Sta/Elev= 30
  4774.6 2243.72  4823.2 2242.49  4844.5 2242.75  4865.6 2241.99  4872.8 2242.28
  4879.8 2241.69  4915.2 2241.68  4922.2 2240.96  4950.5 2240.50  4964.6 2238.60
  4971.8 2236.42  4978.8 2236.33  4985.9 2234.16  5011.5 2233.36  5011.8 2232.86
  5015.3 2232.86  5015.5 2233.36  5042.9 2234.86  5049.5 2238.75  5063.7 2241.28
  5122.5 2242.33  5136.1 2243.53  5143.3 2243.28  5149.5 2244.03  5158.0 2243.74
  5214.4 2245.70  5229.1 2246.80  5243.7 2246.79  5249.9 2247.90  5279.3 2247.71
#Mann=3,-1,0
  4774.6    0.07       0  5011.5    0.07       0  5015.5    0.07       0
Bank Sta=5011.5,5015.5
Exp/Cntr=0.3,0.1

Chan Stop Cuts=-1