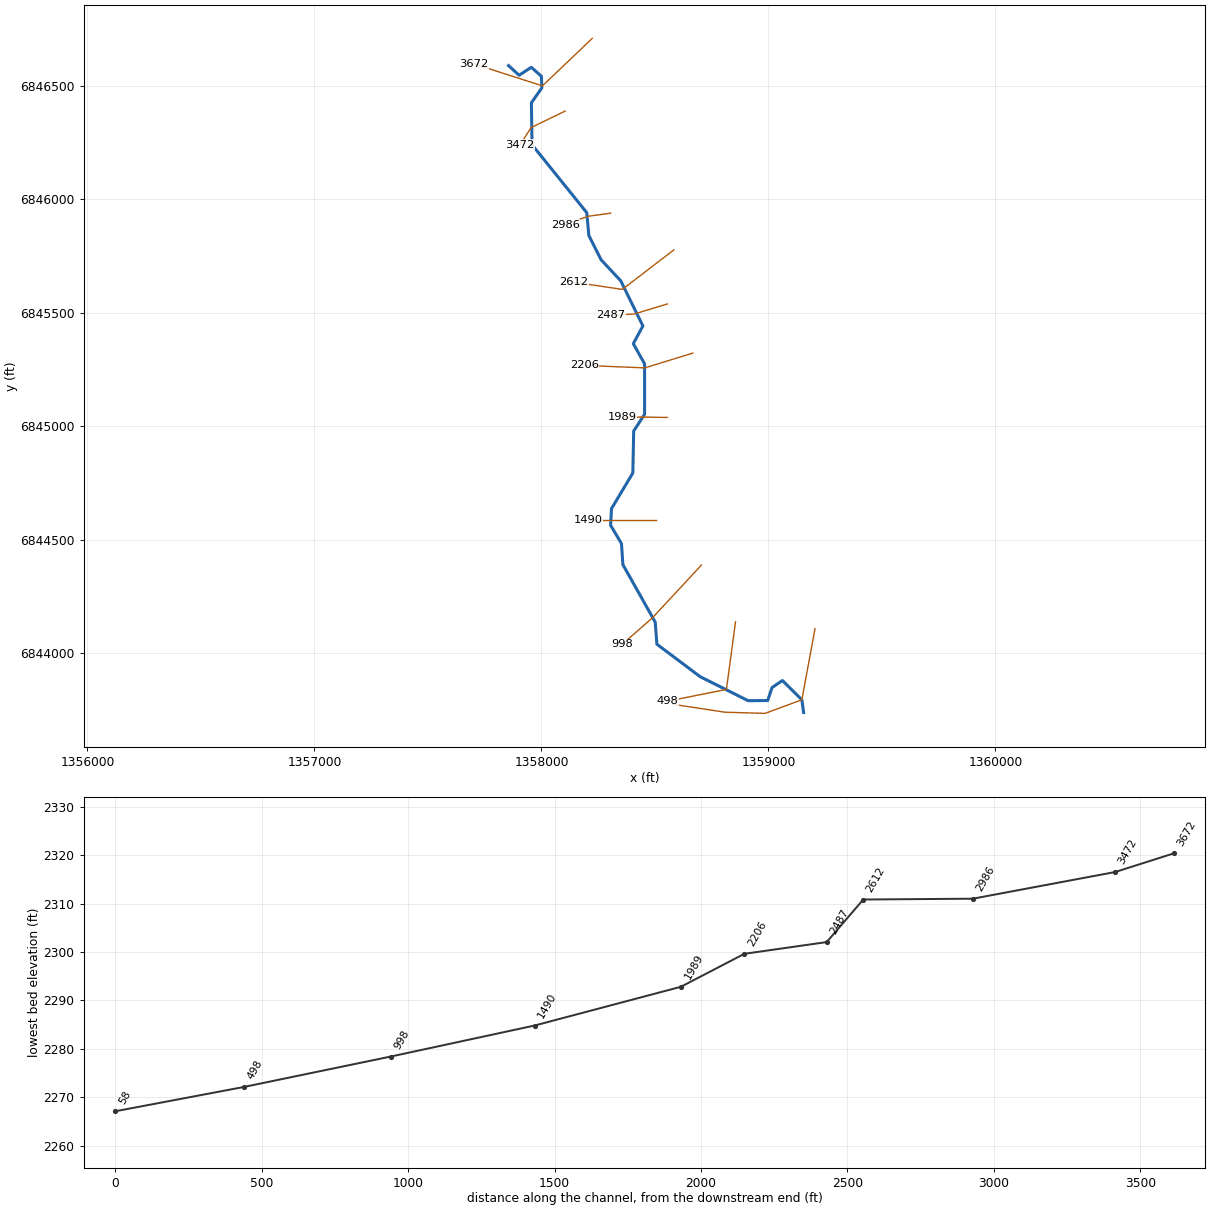
--- Inkman Spring.prj (project) ---

Proj Title=Inkman Spring Base Level Engineering
Current Plan=p01
Default Exp/Contr=0.3,0.1
English Units
Geom File=g01
Flow File=f01
Plan File=p01
Y Axis Title=Elevation
X Axis Title(PF)=Main Channel Distance
X Axis Title(XS)=Station
BEGIN DESCRIPTION:
Inkman Spring
END DESCRIPTION:
DSS Export Rating Curves= 0
DSS Export Rating Curve Sorted= 0
DSS Export Volume Flow Curves= 0
DXF OffsetX= 0
DXF OffsetY= 0
DXF ScaleX= 1
DXF ScaleY= 10

--- Inkman Spring.p01 (plan) ---

Plan Title=Multiple Run
Short Identifier=Multiple
Geom File=g01
Flow File=f01
Subcritical Flow
K Sum by GR= 0
Std Step Tol= 0.01
Critical Tol= 0.01
Num of Std Step Trials= 20
Max Error Tol= 0.3
Flow Tol Ratio= 0.001
Split Flow NTrial= 30
Split Flow Tol= 0.02
Split Flow Ratio= 0.02
Log Output Level= 0
Friction Slope Method= 1
Unsteady Friction Slope Method= 2
Unsteady Bridges Friction Slope Method= 1
Parabolic Critical Depth
Global Vel Dist=  1 , 1 , 1
Global Log Level= 0
CheckData=True
Encroach Param= -1, 0, 0, 0
BEGIN DESCRIPTION:
Multiple Run
END DESCRIPTION:

--- Inkman Spring.f01 (steady flow) ---

Flow Title=Multiple
Program Version=4.10
Number of Profiles= 7
Profile Names=10-year,25-year,50-year,1pct_min,100-year,1pct_plu,500-year
River Rch & RM=Inkman Spring,Reach-1         ,3672
     182     255     315     195     389     776     598
River Rch & RM=Inkman Spring,Reach-1         ,58
     705    1039    1328     841    1678    3349    2720
Boundary for River Rch & Prof#=Inkman Spring,Reach-1         , 1
Up Type= 0
Dn Type= 3
Dn Slope=0.011
Boundary for River Rch & Prof#=Inkman Spring,Reach-1         , 2
Up Type= 0
Dn Type= 3
Dn Slope=0.011
Boundary for River Rch & Prof#=Inkman Spring,Reach-1         , 3
Up Type= 0
Dn Type= 3
Dn Slope=0.011
Boundary for River Rch & Prof#=Inkman Spring,Reach-1         , 4
Up Type= 0
Dn Type= 3
Dn Slope=0.011
Boundary for River Rch & Prof#=Inkman Spring,Reach-1         , 5
Up Type= 0
Dn Type= 3
Dn Slope=0.011
Boundary for River Rch & Prof#=Inkman Spring,Reach-1         , 6
Up Type= 0
Dn Type= 3
Dn Slope=0.011
Boundary for River Rch & Prof#=Inkman Spring,Reach-1         , 7
Up Type= 0
Dn Type= 3
Dn Slope=0.011
DSS Import GetInterval= 0
DSS Import GetPeak= 0
DSS Import FillOption= 0

--- Inkman Spring.g01 (geometry) ---

Geom Title=Existing Conditions
Program Version=4.10

River Reach=Inkman Spring   ,Reach-1
Reach XY= 30
        1357855.        6846588.      1357901.68      6846545.53
      1357955.29      6846580.71      1357999.92      6846540.84
      1358001.66      6846489.81       1357955.7      6846424.09
      1357958.54      6846239.46      1358199.46      6845940.42
      1358208.83      6845839.59      1358263.16      6845731.95
      1358349.15      6845640.29      1358446.93      6845441.31
      1358404.69      6845363.04       1358454.3      6845274.09
      1358454.32      6845051.92      1358406.38      6844978.34
      1358402.65      6844793.52      1358308.67      6844636.42
       1358304.6        6844563.      1358352.53      6844482.43
      1358358.83      6844389.58      1358501.17      6844136.41
      1358508.52      6844039.28      1358698.95      6843896.16
      1358910.64      6843790.22      1358996.66      6843791.03
       1359015.9      6843848.12      1359061.53      6843879.12
      1359147.24      6843794.27        1359155.        6843738.

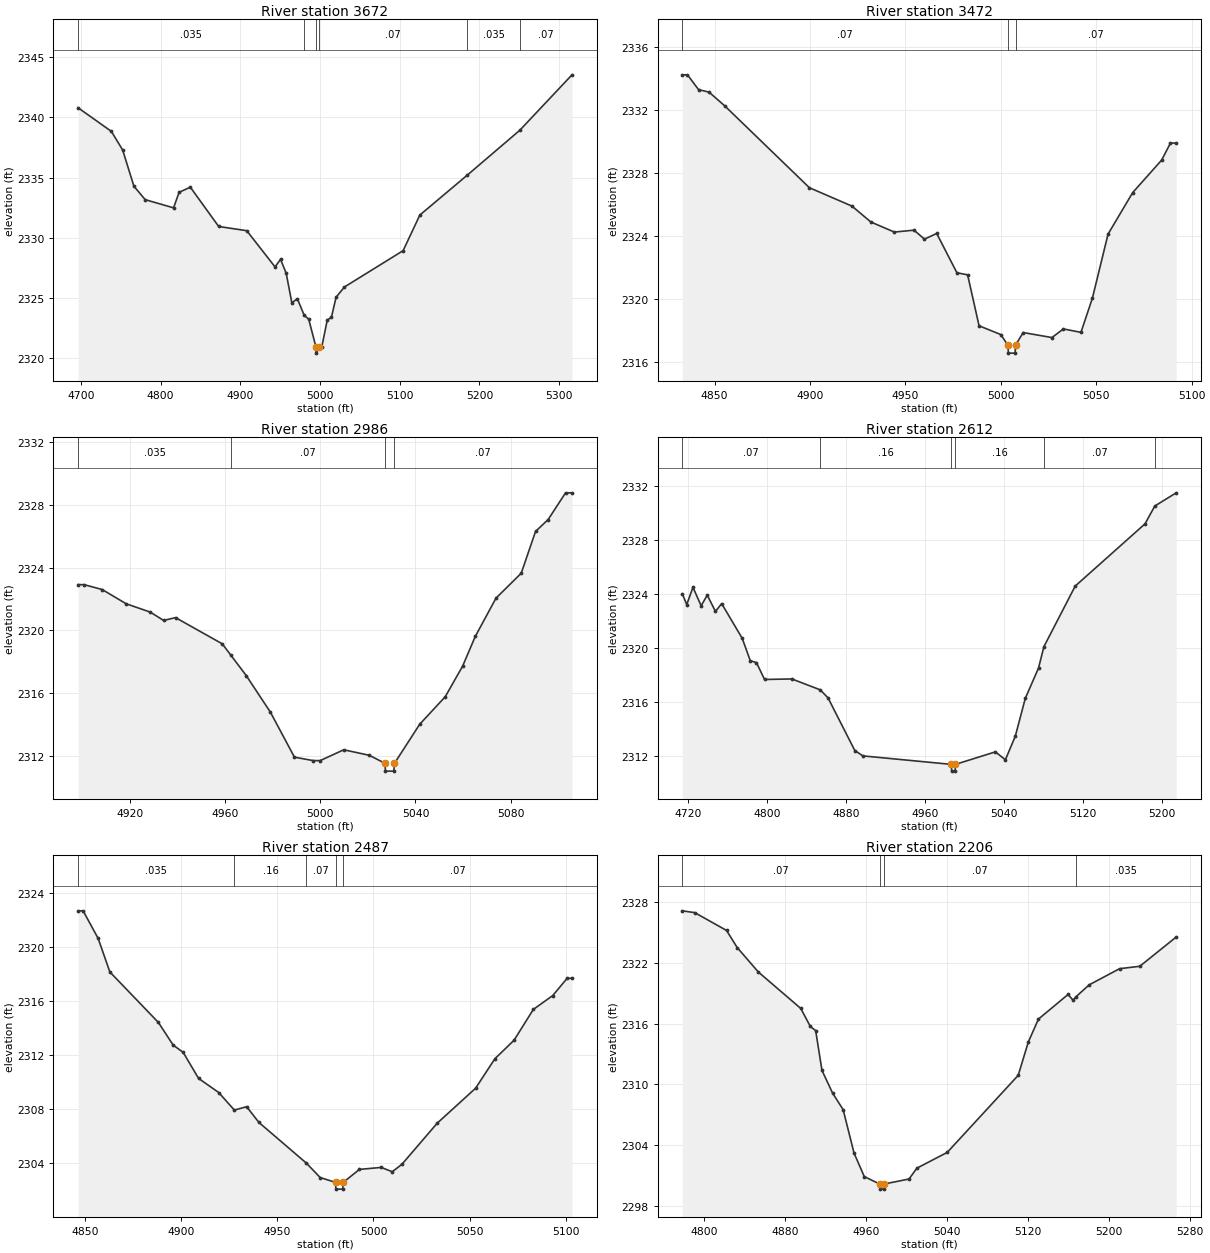
Type RM Length L Ch R = 1 ,3672    ,200,200,200
BEGIN DESCRIPTION:
Inkman Spring 4072
END DESCRIPTION:
XS GIS Cut Line= 3
      1358224.02      6846708.16      1358004.28      6846498.81
      1357703.17      6846595.33
#Sta/Elev= 30
  4696.5  2340.8  4738.2 2338.84  4752.4 2337.29  4766.5 2334.28  4780.7 2333.16
  4816.3 2332.48  4823.2 2333.77  4837.3  2334.2  4872.9 2330.93  4908.1 2330.58
  4943.6 2327.57  4950.5  2328.2  4957.6 2327.04  4964.7 2324.58  4971.6 2324.92
  4980.3 2323.53  4985.8 2323.23    4995  2320.9  4995.2  2320.4    4999  2320.9
  5002.2  2320.9  5009.1 2323.14  5014.4 2323.39  5020.2 2325.05  5030.7  2325.9
  5104.3 2328.92  5125.3 2331.88    5185 2335.21  5250.7 2338.93  5316.2 2343.54
#Mann= 6 ,-1 , 0
  4696.5    .035       0  4980.3     .07       0    4995     .07       0
    4999     .07       0    5185    .035       0  5250.7     .07       0
Bank Sta=4995,4999
XS Rating Curve= 0 ,0
Exp/Cntr=0.3,0.1

Type RM Length L Ch R = 1 ,3472    ,486,486,486
BEGIN DESCRIPTION:
Inkman Spring 2067
END DESCRIPTION:
XS GIS Cut Line= 3
      1358104.97      6846387.99      1357954.78       6846315.2
      1357904.98      6846237.97
#Sta/Elev= 30
  4833.1 2334.25  4835.8 2334.25  4841.6 2333.31  4847.1 2333.15  4855.3 2332.28
  4899.7 2327.07    4922  2325.9  4931.9 2324.89  4944.2 2324.25  4954.5 2324.37
    4960  2323.8  4966.4 2324.16    4977 2321.66  4982.6 2321.53  4988.6 2318.29
    5000 2317.73  5003.7 2317.05    5004 2316.55  5007.5 2316.55  5007.7 2317.05
  5011.7 2317.86  5026.8 2317.54  5032.8 2318.09    5042 2317.87    5048 2320.05
  5056.2 2324.12  5069.1 2326.76  5084.3 2328.83  5088.9 2329.91  5091.9 2329.91
#Mann= 3 ,-1 , 0
  4833.1     .07       0  5003.7     .07       0  5007.7     .07       0
Bank Sta=5003.7,5007.7
XS Rating Curve= 0 ,0
Exp/Cntr=0.3,0.1

Type RM Length L Ch R = 1 ,2986    ,374,374,374
BEGIN DESCRIPTION:
Inkman Spring 2066
END DESCRIPTION:
XS GIS Cut Line= 3
      1358304.97        6845938.      1358204.33      6845924.08
      1358104.98      6845887.99
#Sta/Elev= 30
  4898.4 2322.92  4900.9 2322.92  4908.5 2322.61  4918.6  2321.7  4928.7 2321.17
  4934.3 2320.64  4939.3 2320.82  4958.9 2319.15  4962.5 2318.43    4969 2317.12
  4979.1  2314.8  4989.2 2311.93  4997.1 2311.71    5000 2311.71  5009.9  2312.4
  5020.6 2312.05  5027.2 2311.54  5027.4 2311.04  5030.9 2311.04  5031.2 2311.54
  5041.8 2314.03  5052.5 2315.78  5059.8 2317.73  5065.1 2319.62  5073.8 2322.06
  5084.4 2323.65  5090.4 2326.31  5095.7 2327.07    5103 2328.77  5105.7 2328.77
#Mann= 4 ,-1 , 0
  4898.4    .035       0  4962.5     .07       0  5027.2     .07       0
  5031.2     .07       0
Bank Sta=5027.2,5031.2
XS Rating Curve= 0 ,0
Exp/Cntr=0.3,0.1

Type RM Length L Ch R = 1 ,2612    ,125,125,125
BEGIN DESCRIPTION:
Inkman Spring 4071
END DESCRIPTION:
XS GIS Cut Line= 3
      1358583.17      6845776.08      1358356.16      6845602.12
      1358143.74      6845633.95
#Sta/Elev= 30
    4714 2324.02  4718.5 2323.23  4724.8 2324.51  4733.1 2323.14  4739.3 2323.93
  4747.6 2322.72  4753.9  2323.3  4774.7 2320.73  4782.9 2319.07  4789.2 2318.92
  4797.4 2317.67  4825.1 2317.71  4853.9  2316.9  4861.8  2316.3  4888.9  2312.4
  4897.1    2312  4986.9 2311.37  4987.1 2310.87  4990.6 2310.87  4990.9 2311.37
  5031.5  2312.3  5041.6 2311.71  5051.7 2313.47  5061.8 2316.27  5075.2 2318.52
  5080.7 2320.11  5112.4  2324.6  5183.2 2329.22  5193.1 2330.54  5214.8 2331.52
#Mann= 6 ,-1 , 0
    4714     .07       0  4853.9     .16       0  4986.9     .07       0
  4990.9     .16       0  5080.7     .07       0  5193.1    .035       0
Bank Sta=4986.9,4990.9
XS Rating Curve= 0 ,0
Exp/Cntr=0.3,0.1

Type RM Length L Ch R = 1 ,2487    ,281,281,281
BEGIN DESCRIPTION:
Inkman Spring 2065
END DESCRIPTION:
XS GIS Cut Line= 3
      1358554.97      6845537.99      1358408.02      6845493.63
      1358304.97        6845488.
#Sta/Elev= 30
  4846.5  2322.7  4849.1  2322.7  4856.9 2320.66    4863 2318.17  4888.2 2314.43
  4895.9 2312.75  4901.1 2312.21  4909.1 2310.28  4919.6 2309.23  4927.7 2307.93
  4934.1 2308.18  4940.5 2307.01  4965.2 2303.99  4972.3 2302.93  4980.3 2302.57
  4980.5 2302.07    4984 2302.07  4984.3 2302.57  4992.7 2303.53    5004 2303.68
  5009.8 2303.36  5014.8 2303.91  5033.1 2306.95  5053.1 2309.55  5063.1 2311.73
  5073.1 2313.11  5083.1 2315.39  5093.2 2316.42  5100.7  2317.7  5103.2  2317.7
#Mann= 5 ,-1 , 0
  4846.5    .035       0  4927.7     .16       0  4965.2     .07       0
  4980.3     .07       0  4984.3     .07       0
Bank Sta=4980.3,4984.3
XS Rating Curve= 0 ,0
Exp/Cntr=0.3,0.1

Type RM Length L Ch R = 1 ,2206    ,217,217,217
BEGIN DESCRIPTION:
Inkman Spring 4070
END DESCRIPTION:
XS GIS Cut Line= 3
      1358666.78      6845321.46      1358455.38      6845256.35
       1358189.1      6845267.16
#Sta/Elev= 30
  4778.8 2327.16  4791.1 2326.98  4822.5 2325.22    4833 2323.53  4853.9 2321.11
  4895.8 2317.51  4905.2 2315.73  4910.5 2315.32  4916.7 2311.39  4927.2 2309.14
  4937.6 2307.51  4948.4 2303.21  4958.5 2300.89  4973.8 2300.15  4974.1 2299.65
  4977.6 2299.65  4977.8 2300.15  5002.7 2300.65  5010.4 2301.72  5040.4 2303.28
  5110.5  2310.9  5120.5  2314.2  5130.5 2316.46  5159.7 2318.89  5164.7 2318.32
  5167.6 2318.67  5180.5 2319.84  5210.6 2321.44  5230.6 2321.68  5266.5 2324.57
#Mann= 4 ,-1 , 0
  4778.8     .07       0  4973.8     .07       0  4977.8     .07       0
  5167.6    .035       0
Bank Sta=4973.8,4977.8
XS Rating Curve= 0 ,0
Exp/Cntr=0.3,0.1

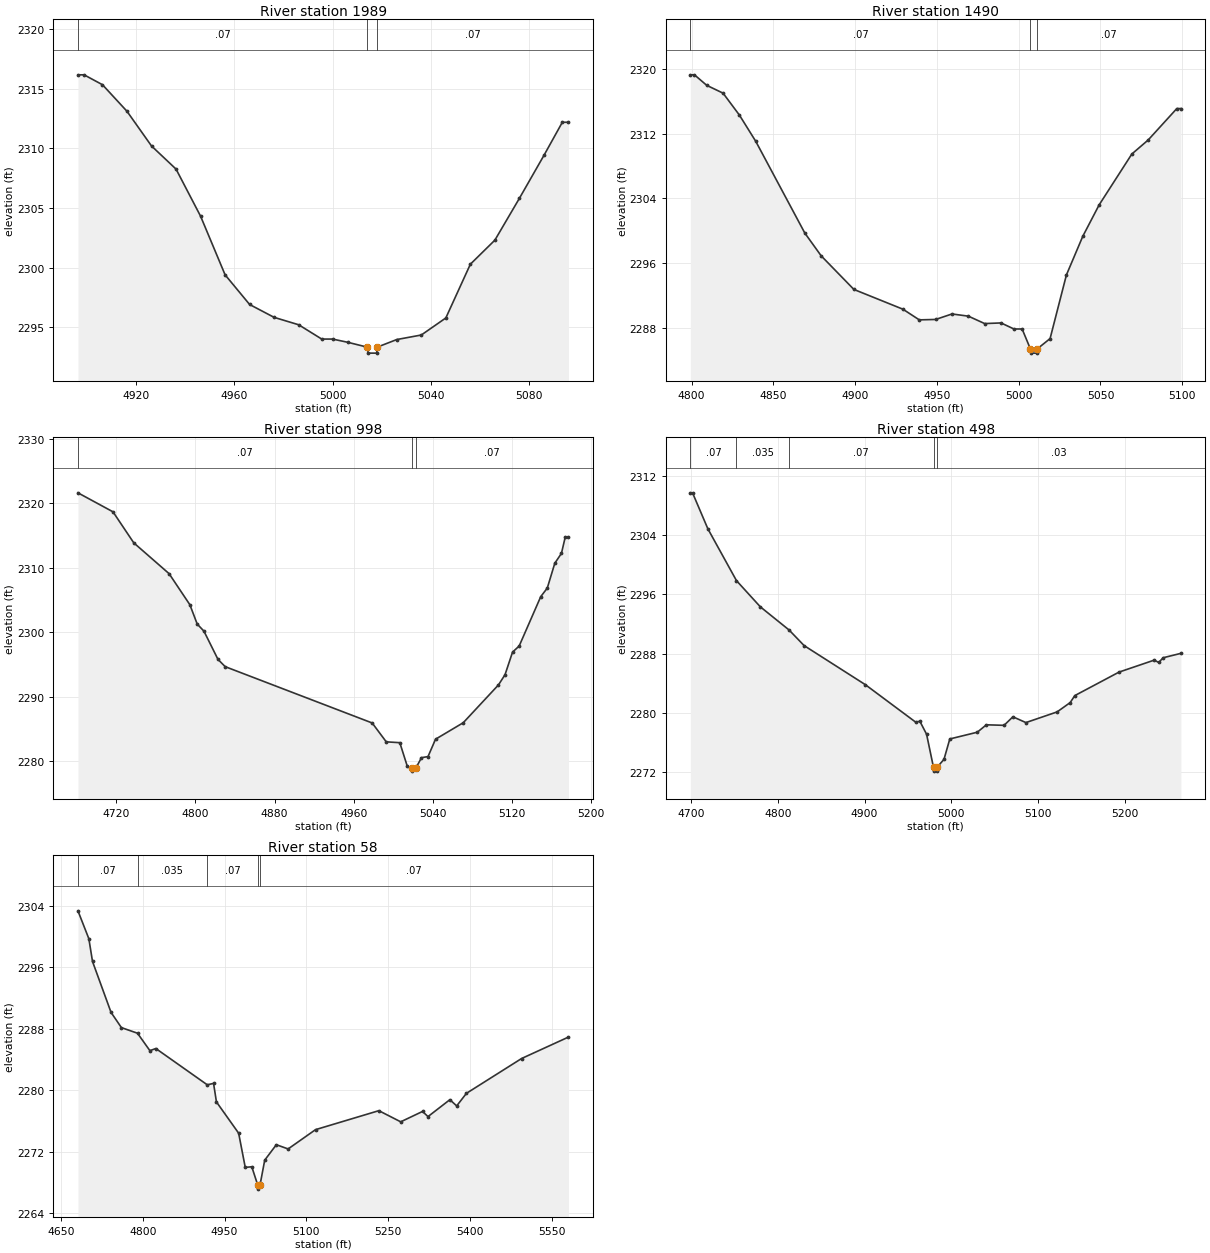
Type RM Length L Ch R = 1 ,1989    ,499,499,499
BEGIN DESCRIPTION:
Inkman Spring 2064
END DESCRIPTION:
XS GIS Cut Line= 3
      1358555.01        6845038.      1358451.22      6845039.57
      1358355.03        6845038.
#Sta/Elev= 27
  4896.2 2316.18  4898.7 2316.18  4906.2 2315.35  4916.2 2313.12  4926.2 2310.21
  4936.2 2308.27  4946.2 2304.32  4956.2  2299.4  4966.2 2296.91  4976.2 2295.83
  4986.2 2295.21  4995.6 2294.01    5000 2294.01  5006.2 2293.74  5014.2 2293.33
  5014.5 2292.83    5018 2292.83  5018.2 2293.33  5026.2 2293.97  5036.2 2294.35
  5046.2 2295.78  5056.2 2300.29  5066.2 2302.31  5076.2 2305.82  5086.2 2309.42
  5093.7  2312.2  5096.2  2312.2
#Mann= 3 ,-1 , 0
  4896.2     .07       0  5014.2     .07       0  5018.2     .07       0
Bank Sta=5014.2,5018.2
XS Rating Curve= 0 ,0
Exp/Cntr=0.3,0.1

Type RM Length L Ch R = 1 ,1490    ,492,492,492
BEGIN DESCRIPTION:
Inkman Spring 2063
END DESCRIPTION:
XS GIS Cut Line= 3
      1358504.98        6844588.      1358304.18        6844588.
      1358204.98        6844588.
#Sta/Elev= 30
  4799.2  2319.3  4801.7  2319.3  4809.2    2318  4819.2 2317.03  4829.2 2314.31
  4839.2 2311.06  4869.2  2299.7  4879.2 2296.88  4899.2 2292.72  4929.2 2290.27
  4939.2 2288.95  4949.2    2289  4959.2 2289.68  4969.2 2289.41  4979.2 2288.49
  4989.2 2288.57  4997.1 2287.82  5002.1 2287.82  5007.2 2285.33  5007.4 2284.83
  5010.9 2284.83  5011.2 2285.33  5019.2 2286.63  5029.2 2294.52  5039.2  2299.3
  5049.2 2303.19  5069.2 2309.49  5079.2 2311.23  5096.7 2315.12  5099.2 2315.12
#Mann= 3 ,-1 , 0
  4799.2     .07       0  5007.2     .07       0  5011.2     .07       0
Bank Sta=5007.2,5011.2
XS Rating Curve= 0 ,0
Exp/Cntr=0.3,0.1

Type RM Length L Ch R = 1 ,998     ,500,500,500
BEGIN DESCRIPTION:
Inkman Spring 2062
END DESCRIPTION:
XS GIS Cut Line= 3
      1358705.01      6844388.01      1358488.16       6844154.6
        1358355.        6844038.
#Sta/Elev= 30
  4681.4 2321.65  4716.8  2318.7  4737.8 2313.88  4773.5 2309.09  4794.5 2304.26
  4801.9 2301.26  4808.7 2300.16  4822.9 2295.77  4830.2 2294.64  4978.7 2285.89
  4992.9 2282.96  5006.6 2282.83  5014.2 2279.15  5018.9 2278.91  5019.1 2278.41
  5022.9 2278.91  5028.5  2280.5  5035.1 2280.67  5042.7 2283.37  5070.7 2285.93
  5106.3 2291.81  5112.9 2293.39  5120.5  2296.9  5127.2 2297.85    5149 2305.52
  5155.6 2306.85  5163.2 2310.71  5169.9 2312.24  5173.7 2314.74    5177 2314.74
#Mann= 3 ,-1 , 0
  4681.4     .07       0  5018.9     .07       0  5022.9     .07       0
Bank Sta=5018.9,5022.9
XS Rating Curve= 0 ,0
Exp/Cntr=0.3,0.1

Type RM Length L Ch R = 1 ,498     ,440,440,440
BEGIN DESCRIPTION:
Inkman Spring 2061
END DESCRIPTION:
XS GIS Cut Line= 3
        1358855.      6844138.02      1358814.84      6843839.81
      1358554.96      6843787.99
#Sta/Elev= 30
  4699.1 2309.69  4701.6 2309.69  4719.3 2304.83  4752.3 2297.84  4779.8 2294.31
    4813 2291.18  4830.3 2289.08  4900.9 2283.81  4958.9 2278.76  4963.9 2278.86
  4971.6 2277.12  4979.6 2272.64  4979.9 2272.14  4983.4 2272.14  4983.6 2272.64
  4991.7 2273.73  4998.4 2276.48  5030.1 2277.39  5040.6 2278.39    5061 2278.32
  5071.2 2279.47  5086.2 2278.69  5122.2 2280.13  5137.3 2281.39  5142.6 2282.33
  5193.6  2285.5  5234.3 2287.12  5239.4  2286.8  5244.6 2287.44    5265 2288.03
#Mann= 5 ,-1 , 0
  4699.1     .07       0  4752.3    .035       0    4813     .07       0
  4979.6     .03       0  4983.6     .03       0
Bank Sta=4979.6,4983.6
XS Rating Curve= 0 ,0
Exp/Cntr=0.3,0.1

Type RM Length L Ch R = 1 ,58      ,0,0,0
BEGIN DESCRIPTION:
Long Branch 4472
END DESCRIPTION:
XS GIS Cut Line= 5
      1359205.16      6844107.66      1359147.24      6843794.27
      1358984.68      6843734.41       1358807.6      6843739.61
      1358580.12      6843774.34
#Sta/Elev= 30
  4681.3 2303.33  4701.3  2299.7    4708 2296.74    4742 2290.11    4761 2288.13
  4790.5  2287.4  4813.2 2285.13  4824.1 2285.41  4918.3 2280.69  4929.9 2280.87
  4935.2 2278.46  4975.9 2274.39    4988 2269.94    5000 2270.02    5011 2267.61
  5011.3 2267.11    5015 2267.61  5023.7 2270.88    5045 2272.89  5066.6 2272.34
  5116.8 2274.85  5232.9 2277.32    5273 2275.87    5313 2277.22    5323 2276.55
  5363.1 2278.75  5375.6 2277.94  5393.5 2279.58  5494.6 2284.11  5580.5  2286.9
#Mann= 5 ,-1 , 0
  4681.3     .07       0  4790.5    .035       0  4918.3     .07       0
    5011     .07       0    5015     .07       0
Bank Sta=5011,5015
XS Rating Curve= 0 ,0
Exp/Cntr=0.3,0.1

Chan Stop Cuts=-1
Use User Specified Reach Order=0
Composite Channel Slope=5