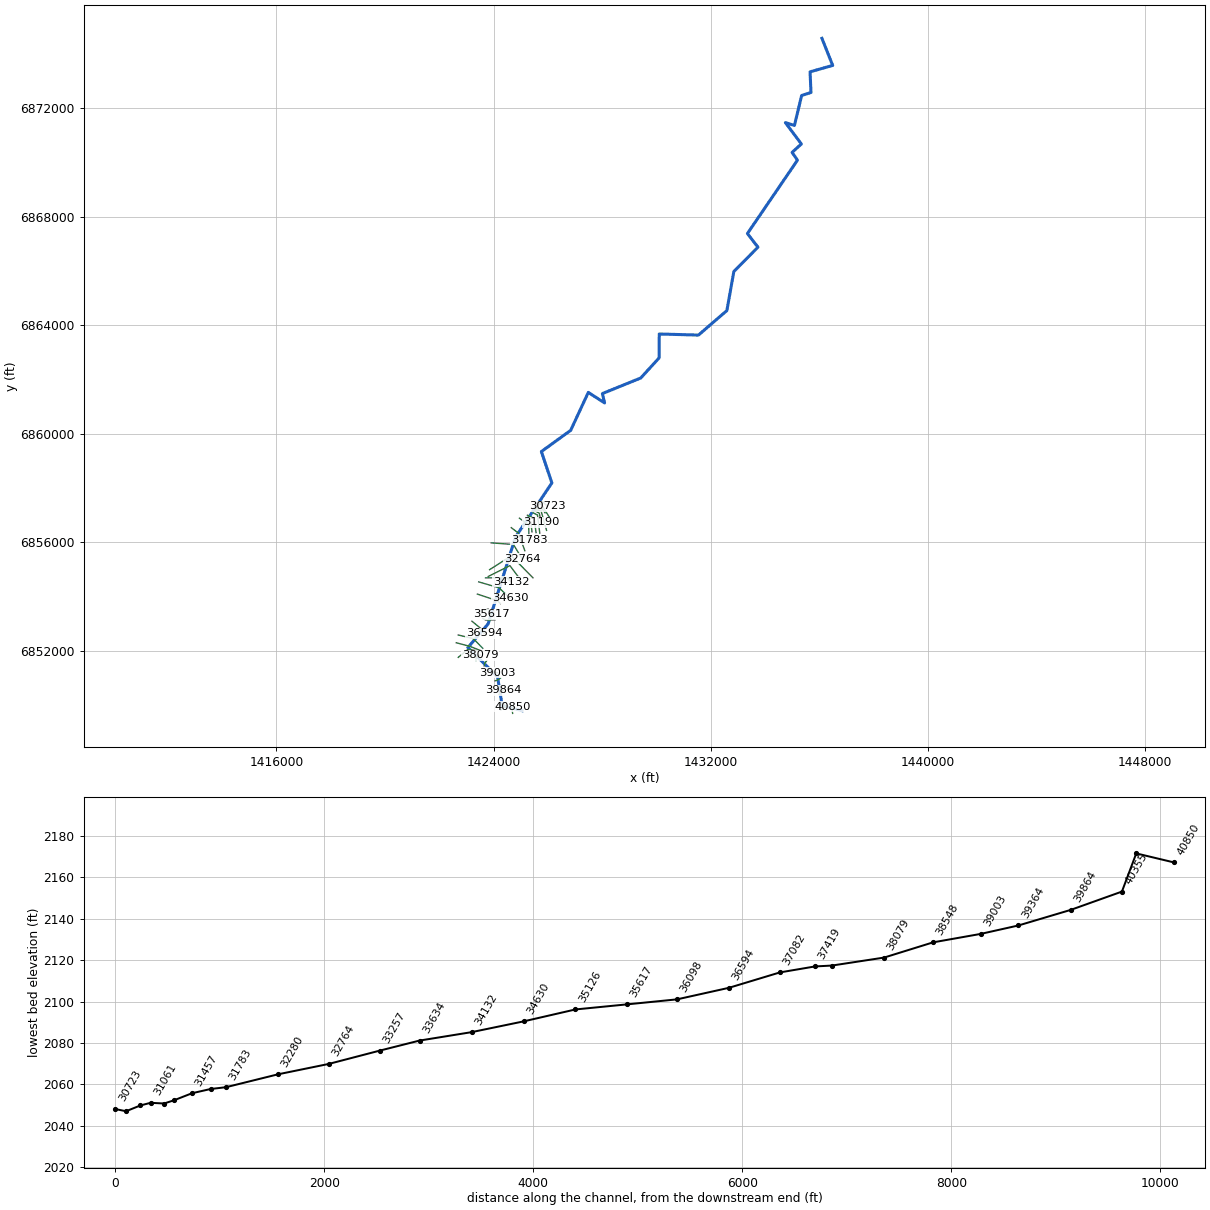
--- Little Stink Creek.prj (project) ---

Proj Title=Little Stink Creek Base Level Engineering
Current Plan=p01
Default Exp/Contr=0.3,0.1
English Units
Geom File=g01
Flow File=f01
Plan File=p01
Y Axis Title=Elevation
X Axis Title(PF)=Main Channel Distance
X Axis Title(XS)=Station
BEGIN DESCRIPTION:
Little Stink Creek
END DESCRIPTION:
DSS Export Rating Curves= 0
DSS Export Rating Curve Sorted= 0
DSS Export Volume Flow Curves= 0
DXF OffsetX= 0
DXF OffsetY= 0
DXF ScaleX= 1
DXF ScaleY= 10

--- Little Stink Creek.p01 (plan) ---

Plan Title=Multiple Run
Short Identifier=Multiple
Geom File=g01
Flow File=f01
Subcritical Flow
K Sum by GR= 0
Std Step Tol= 0.01
Critical Tol= 0.01
Num of Std Step Trials= 20
Max Error Tol= 0.3
Flow Tol Ratio= 0.001
Split Flow NTrial= 30
Split Flow Tol= 0.02
Split Flow Ratio= 0.02
Log Output Level= 0
Friction Slope Method= 1
Unsteady Friction Slope Method= 2
Unsteady Bridges Friction Slope Method= 1
Parabolic Critical Depth
Global Vel Dist=  1 , 1 , 1
Global Log Level= 0
CheckData=True
Encroach Param= -1, 0, 0, 0
BEGIN DESCRIPTION:
Multiple Run
END DESCRIPTION:

--- Little Stink Creek.f01 (steady flow) ---

Flow Title=Multiple
Number of Profiles=7
Profile Names=10-year,25-year,50-year,1pct_min,100-year,1pct_plu,500-year
River Rch & RM= Little Stink Cre,Reach-1,40850
     561     834    1076     690    1376    2745    2280
River Rch & RM= Little Stink Cre,Reach-1,29572
     615     918    1187     763    1522    3037    2536
River Rch & RM= Little Stink Cre,Reach-1,28442
     773    1168    1521     984    1964    3918    3315
River Rch & RM= Little Stink Cre,Reach-1,27104
     807    1214    1577    1016    2027    4044    3395
River Rch & RM= Little Stink Cre,Reach-1,20178
     873    1314    1708    1100    2195    4380    3678
River Rch & RM= Little Stink Cre,Reach-1,15745
    1300    1982    2597    1686    3363    6710    5717
River Rch & RM= Little Stink Cre,Reach-1,11823
    1244    1877    2443    1573    3139    6264    5256
Boundary for River Rch & Prof#=Little Stink Cre,Reach-1,1
Up Type=0
Dn Type=3
Dn Slope=0.005
Boundary for River Rch & Prof#=Little Stink Cre,Reach-1,2
Up Type=0
Dn Type=3
Dn Slope=0.005
Boundary for River Rch & Prof#=Little Stink Cre,Reach-1,3
Up Type=0
Dn Type=3
Dn Slope=0.005
Boundary for River Rch & Prof#=Little Stink Cre,Reach-1,4
Up Type=0
Dn Type=3
Dn Slope=0.005
Boundary for River Rch & Prof#=Little Stink Cre,Reach-1,5
Up Type=0
Dn Type=3
Dn Slope=0.005
Boundary for River Rch & Prof#=Little Stink Cre,Reach-1,6
Up Type=0
Dn Type=3
Dn Slope=0.005
Boundary for River Rch & Prof#=Little Stink Cre,Reach-1,7
Up Type=0
Dn Type=3
Dn Slope=0.005

--- Little Stink Creek.g01 (geometry) ---

Geom Title=Existing Conditions
Program Version=4.10

River Reach=Little Stink Cre,Reach-1
Reach XY= 30
        1425055.        6849788.      1424318.62      6849974.78
      1424149.54      6851040.45      1423054.63      6852115.25
       1423801.9      6852989.65      1424810.48      6856190.45
      1426151.25      6858189.55      1425763.98      6859344.66
      1426844.52       6860128.2      1427494.48      6861527.58
      1428093.81      6861139.51      1428012.79       6861484.5
      1429425.51      6862057.73      1430103.29      6862798.86
      1430110.19      6863682.56       1431553.5      6863641.47
      1432601.94      6864546.28      1432858.54      6865986.54
      1433747.22      6866884.57      1433358.64      6867386.38
      1435202.95      6870093.45      1435006.39      6870381.47
      1435347.51      6870691.14      1434757.97      6871480.42
      1435091.77      6871374.27      1435357.91      6872480.09
      1435701.85      6872589.63      1435668.37      6873351.37
        1436502.      6873589.46        1436105.        6874588.

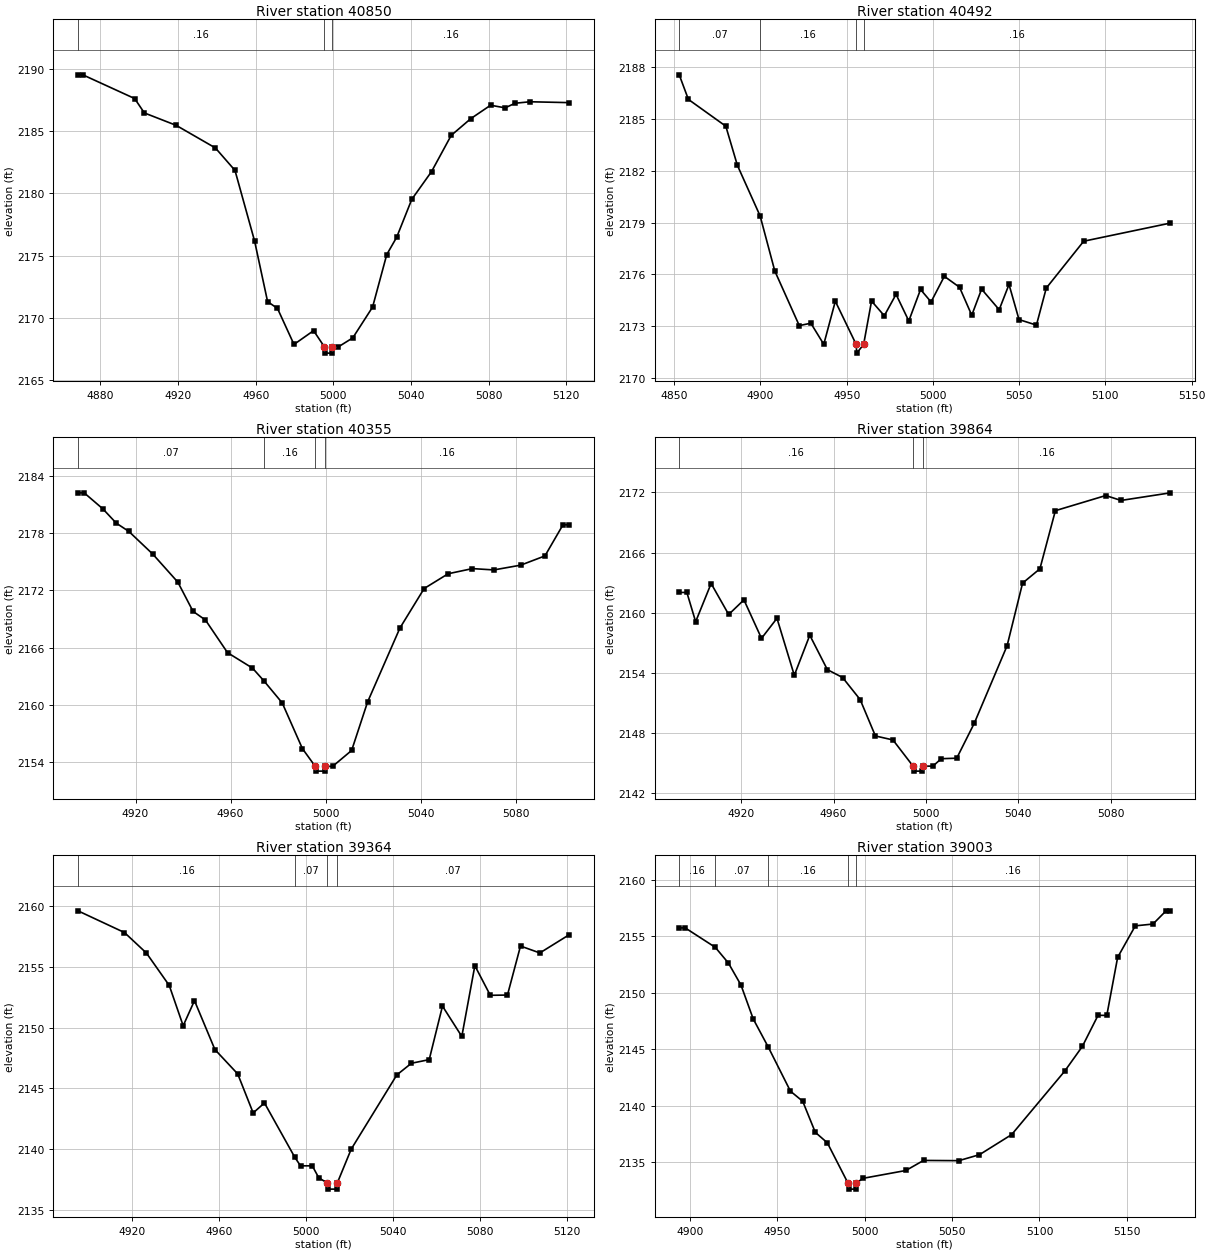
Type RM Length L Ch R = 1 ,40850   ,358,358,358
BEGIN DESCRIPTION:
Little Stink Creek 57.0
END DESCRIPTION:
XS GIS Cut Line= 3
        1424705.      6849688.01      1424685.13      6849818.11
        1424705.      6849937.97
#Sta/Elev= 30
  4868.4 2189.56  4870.9 2189.56  4897.6 2187.65  4902.6 2186.49    4919 2185.49
  4939.2 2183.67  4949.3 2181.86  4959.4 2176.17  4966.1 2171.29  4971.2 2170.74
  4979.7 2167.84  4989.8 2168.95  4995.4 2167.64  4995.6 2167.14  4999.2 2167.14
  4999.5 2167.64  5002.5 2167.64    5010 2168.37  5020.2 2170.85  5027.5 2175.08
  5032.6 2176.47  5040.4 2179.53  5050.6 2181.77  5060.7 2184.68  5070.8 2186.03
    5081 2187.11  5088.5  2186.9  5093.6 2187.27  5101.3 2187.39  5121.5 2187.32
#Mann= 3 ,-1 , 0
  4868.4     .16       0  4995.4     .07       0  4999.5     .16       0
Bank Sta=4995.4,4999.5
XS Rating Curve= 0 ,0
Exp/Cntr=0.3,0.1

Type RM Length L Ch R = 1 ,40492   ,137,137,137
BEGIN DESCRIPTION:
Little Stink Creek 56.1
END DESCRIPTION:
XS GIS Cut Line= 3
      1424272.27      6849812.82      1424381.59      6849911.25
      1424501.35      6849979.21
#Sta/Elev= 30
  4852.9 2187.54  4858.2 2186.12  4879.9 2184.57  4886.6 2182.31  4899.8 2179.38
  4908.3  2176.2  4922.5 2173.04  4929.2 2173.18  4936.7 2171.96  4943.4 2174.45
  4955.5 2171.95  4955.8 2171.45  4959.8 2171.95  4964.4 2174.46  4971.8 2173.61
  4978.6 2174.85    4986 2173.31  4992.8 2175.13  4998.9 2174.41  5006.6 2175.89
  5015.4 2175.26  5022.5 2173.64  5028.2 2175.15  5038.4 2173.96  5044.1 2175.42
  5049.9 2173.39    5060 2173.07  5065.7 2175.21  5087.4 2177.92  5137.7 2178.97
#Mann= 4 ,-1 , 0
  4852.9     .07       0  4899.8     .16       0  4955.5     .07       0
  4959.8     .16       0
Bank Sta=4955.5,4959.8
XS Rating Curve= 0 ,0
Exp/Cntr=0.3,0.1

Type RM Length L Ch R = 1 ,40355   ,491,491,491
BEGIN DESCRIPTION:
Little Stink Creek 56.0
END DESCRIPTION:
XS GIS Cut Line= 3
      1424205.01        6849988.      1424304.33      6850019.54
      1424405.05      6850038.01
#Sta/Elev= 30
  4895.8 2182.24  4898.4 2182.24  4906.3 2180.55  4911.9 2179.06  4917.2 2178.19
  4927.3  2175.8  4937.8 2172.87  4944.2  2169.8  4949.4  2168.9  4958.7 2165.47
  4969.2 2163.85  4973.9 2162.54  4981.7  2160.2  4990.2  2155.4  4995.6 2153.54
  4995.9 2153.04  4999.6 2153.04  4999.9 2153.54  5002.9 2153.54  5010.9 2155.21
  5017.6 2160.29  5031.2 2168.05  5041.4  2172.2  5051.5 2173.75  5061.7 2174.29
  5070.7 2174.15    5082 2174.65  5092.2 2175.62  5099.8 2178.89  5102.4 2178.89
#Mann= 4 ,-1 , 0
  4895.8     .07       0  4973.9     .16       0  4995.6     .07       0
  4999.9     .16       0
Bank Sta=4995.6,4999.9
XS Rating Curve= 0 ,0
Exp/Cntr=0.3,0.1

Type RM Length L Ch R = 1 ,39864   ,500,500,500
BEGIN DESCRIPTION:
Little Stink Creek 55.0
END DESCRIPTION:
XS GIS Cut Line= 3
      1424204.99      6850387.99       1424275.5       6850468.2
        1424355.        6850538.
#Sta/Elev= 30
  4893.2 2162.02  4896.5 2162.02  4900.3  2159.1    4907 2162.91  4914.6 2159.82
  4921.2 2161.28  4928.8 2157.44  4935.5 2159.44    4943 2153.75  4949.7 2157.75
  4957.3 2154.32  4963.9 2153.53  4971.5 2151.33  4978.1  2147.7  4985.7  2147.3
  4994.4 2144.69  4994.7 2144.19  4998.4 2144.19  4998.7 2144.69    5003 2144.69
  5006.6 2145.43  5013.3 2145.48  5020.9 2148.97  5035.1  2156.7  5041.8 2162.95
  5049.3 2164.38    5056 2170.18  5077.8 2171.69  5084.4  2171.2  5105.8 2171.96
#Mann= 3 ,-1 , 0
  4893.2     .16       0  4994.4     .07       0  4998.7     .16       0
Bank Sta=4994.4,4998.7
XS Rating Curve= 0 ,0
Exp/Cntr=0.3,0.1

Type RM Length L Ch R = 1 ,39364   ,361,361,361
BEGIN DESCRIPTION:
Little Stink Creek 54.0
END DESCRIPTION:
XS GIS Cut Line= 3
      1424054.98      6850887.99      1424155.04      6850919.83
        1424255.        6850988.
#Sta/Elev= 30
    4895 2159.62  4916.4 2157.83  4926.5 2156.14    4937 2153.47  4943.4 2150.15
  4948.6 2152.22    4958 2148.19  4968.5 2146.18  4975.6 2142.97  4980.8 2143.79
  4994.8  2139.3  4997.4 2138.61  5002.8 2138.61  5005.8 2137.62  5009.8 2137.19
  5010.2 2136.69    5014 2136.69  5014.3 2137.19  5020.7 2139.98  5041.7  2146.1
  5048.4 2147.06  5056.6 2147.36  5062.7 2151.77  5071.6 2149.27  5077.6  2155.1
  5084.7 2152.66  5092.6 2152.68  5098.6 2156.72  5107.5 2156.15    5121 2157.65
#Mann= 4 ,-1 , 0
    4895     .16       0  4994.8     .07       0  5009.8     .07       0
  5014.3     .07       0
Bank Sta=5009.8,5014.3
XS Rating Curve= 0 ,0
Exp/Cntr=0.3,0.1

Type RM Length L Ch R = 1 ,39003   ,455,455,455
BEGIN DESCRIPTION:
Little Stink Creek 53.0
END DESCRIPTION:
XS GIS Cut Line= 3
      1423905.03      6851138.03      1423981.62      6851211.31
      1424154.96      6851188.01
#Sta/Elev= 30
    4894 2155.75  4897.4 2155.75  4914.6 2154.03  4922.1 2152.64  4929.3 2150.69
  4936.3 2147.69    4945 2145.17  4957.6 2141.29  4964.6  2140.4  4971.8 2137.65
  4978.7 2136.72  4990.6 2133.12  4990.9 2132.62  4994.8 2132.62  4995.1 2133.12
  4998.9 2133.57  5023.6 2134.27  5033.7 2135.16  5053.9 2135.14  5065.7 2135.67
  5084.1 2137.45  5114.4 2143.06  5124.5 2145.25  5133.5 2148.01  5138.5    2148
  5144.7 2153.14  5154.8 2155.93  5164.9 2156.09  5172.4 2157.26  5174.9 2157.26
#Mann= 5 ,-1 , 0
    4894     .16       0  4914.6     .07       0    4945     .16       0
  4990.6     .07       0  4995.1     .16       0
Bank Sta=4990.6,4995.1
XS Rating Curve= 0 ,0
Exp/Cntr=0.3,0.1

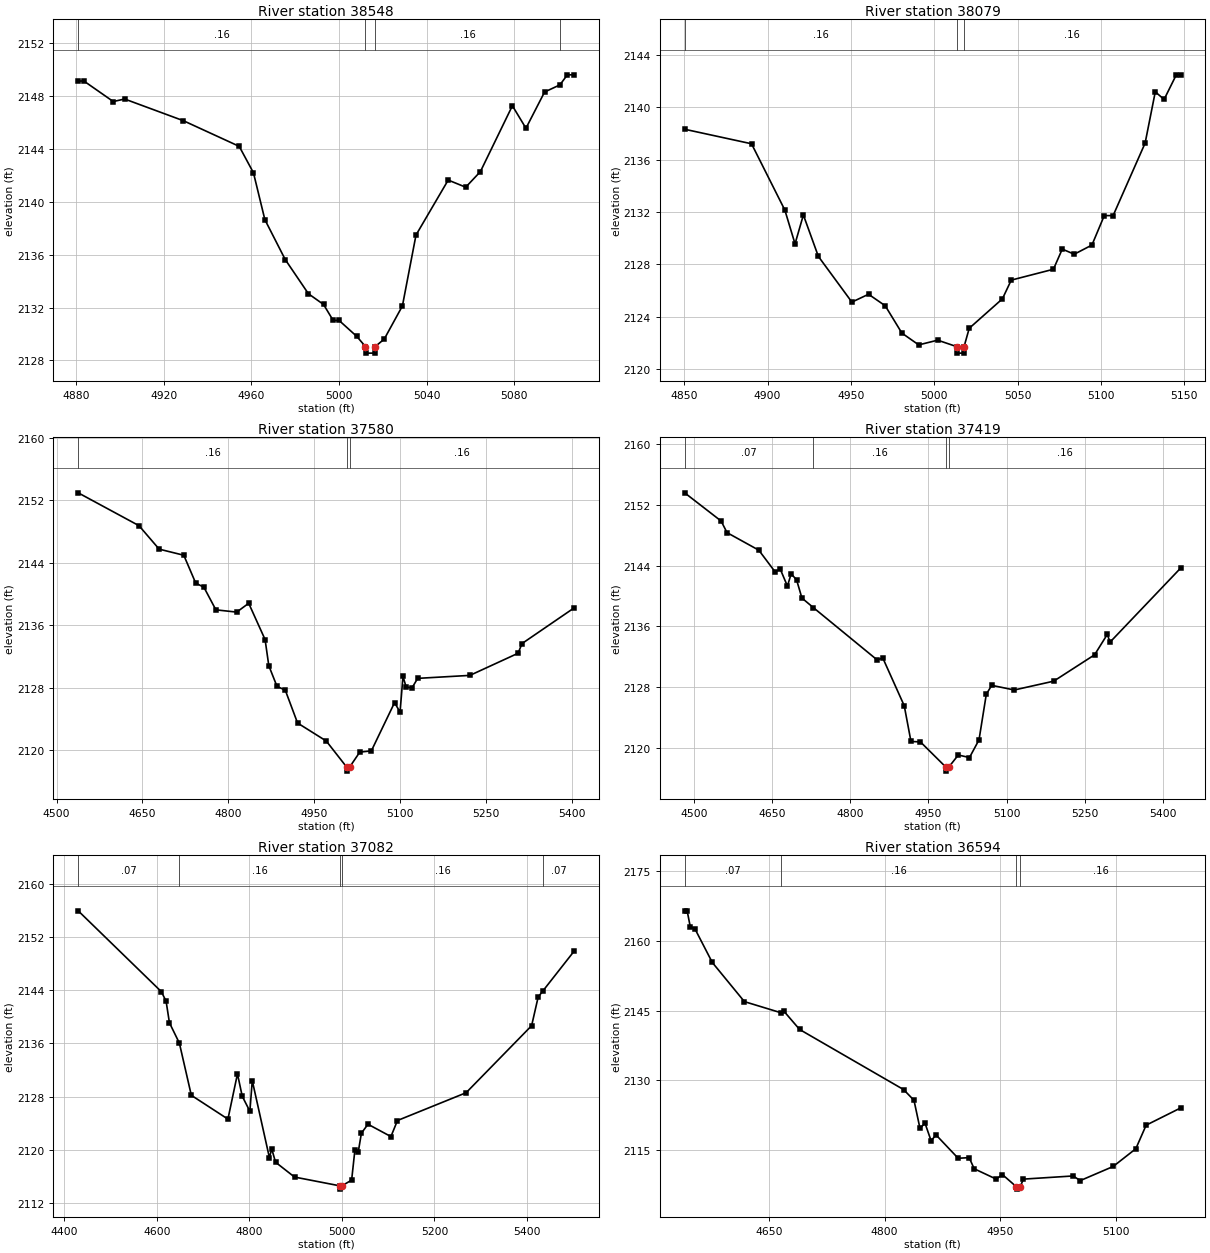
Type RM Length L Ch R = 1 ,38548   ,469,469,469
BEGIN DESCRIPTION:
Little Stink Creek 52.0
END DESCRIPTION:
XS GIS Cut Line= 3
      1423655.01      6851438.05      1423691.68      6851551.36
      1423754.99      6851637.99
#Sta/Elev= 30
  4880.9 2149.13  4883.5 2149.13  4896.9 2147.58  4902.1 2147.77  4928.9 2146.13
  4954.4 2144.19  4960.9 2142.19  4966.1 2138.65  4975.4 2135.63    4986 2133.04
  4992.9 2132.23  4997.3 2131.02    5000 2131.02  5008.1 2129.81    5012 2129.05
  5012.3 2128.55  5016.2 2128.55  5016.5 2129.05  5020.6 2129.61  5028.9 2132.12
  5035.1 2137.48  5049.8 2141.64  5057.8  2141.1  5064.5 2142.28  5079.1 2147.26
  5085.3 2145.56  5093.8  2148.3  5100.8 2148.84  5104.2  2149.6  5107.3  2149.6
#Mann= 4 ,-1 , 0
  4880.9     .16       0    5012     .07       0  5016.5     .16       0
  5100.8     .07       0
Bank Sta=5012,5016.5
XS Rating Curve= 0 ,0
Exp/Cntr=0.3,0.1

Type RM Length L Ch R = 1 ,38079   ,499,499,499
BEGIN DESCRIPTION:
Little Stink Creek 51.0
END DESCRIPTION:
XS GIS Cut Line= 3
        1423355.      6851638.03      1423366.13      6851787.31
      1423504.97      6851837.99
#Sta/Elev= 30
  4850.3 2138.32  4890.4 2137.21  4910.4 2132.14  4916.5 2129.56  4921.5 2131.77
  4930.5  2128.6  4950.6 2125.11  4960.6 2125.71  4970.6 2124.83  4980.6 2122.74
  4990.7 2121.84  5002.1  2122.2  5013.4 2121.71  5013.7 2121.21  5017.6 2121.21
  5017.9 2121.71    5021 2123.11  5040.9 2125.36  5046.2 2126.79  5071.5 2127.62
  5076.8 2129.16    5084 2128.77  5094.6 2129.47    5102 2131.72  5107.3 2131.72
  5126.5 2137.26  5132.6 2141.18  5137.9  2140.6  5145.2 2142.48  5147.8 2142.48
#Mann= 3 ,-1 , 0
  4850.3     .16       0  5013.4     .07       0  5017.9     .16       0
Bank Sta=5013.4,5017.9
XS Rating Curve= 0 ,0
Exp/Cntr=0.3,0.1

Type RM Length L Ch R = 1 ,37580   ,161,161,161
BEGIN DESCRIPTION:
Little Stink Creek 50.0
END DESCRIPTION:
XS GIS Cut Line= 3
      1422700.32      6851753.56      1423056.05      6852048.66
      1423454.97        6851988.
#Sta/Elev= 30
  4537.8 2152.94  4643.9 2148.74  4679.1 2145.74  4722.1 2144.96  4742.9  2141.4
  4757.2 2140.87  4778.1 2137.98  4814.5 2137.69  4835.4 2138.82    4864 2134.18
  4870.5 2130.84  4884.8 2128.19  4899.2 2127.72  4920.7 2123.51  4970.8 2121.21
  5006.6 2117.86    5007 2117.36  5011.4 2117.86  5029.3 2119.79  5049.5 2119.95
    5090 2126.12  5099.6  2124.9  5104.7 2129.47  5110.2 2128.12  5120.3 2127.99
  5130.4 2129.22  5221.5  2129.6  5305.6 2132.43  5312.5 2133.67  5403.5 2138.23
#Mann= 3 ,-1 , 0
  4537.8     .16       0  5006.6     .07       0  5011.4     .16       0
Bank Sta=5006.6,5011.4
XS Rating Curve= 0 ,0
Exp/Cntr=0.3,0.1

Type RM Length L Ch R = 1 ,37419   ,337,337,337
BEGIN DESCRIPTION:
Little Stink Creek 49.1
END DESCRIPTION:
XS GIS Cut Line= 3
      1422627.39      6852292.59      1423128.31      6852161.08
      1423531.85      6852001.63
#Sta/Elev= 30
  4482.1 2153.57    4552 2149.86  4563.4 2148.33  4624.4 2146.02  4655.4 2143.19
  4665.7  2143.5  4679.3 2141.29  4686.4 2142.91  4696.8 2142.13  4707.1 2139.72
  4729.1 2138.46  4851.8 2131.56  4862.2 2131.85  4903.5 2125.54  4916.4 2120.84
  4934.5 2120.79  4983.8 2117.44  4984.2 2116.94  4988.6 2117.44  5007.2 2119.06
  5028.7 2118.73    5047 2121.06    5061 2127.07  5071.4 2128.23  5114.7 2127.62
  5190.3 2128.78  5268.8 2132.25  5293.1 2134.93  5298.5 2133.92  5433.9 2143.66
#Mann= 4 ,-1 , 0
  4482.1     .07       0  4729.1     .16       0  4983.8     .07       0
  4988.6     .16       0
Bank Sta=4983.8,4988.6
XS Rating Curve= 0 ,0
Exp/Cntr=0.3,0.1

Type RM Length L Ch R = 1 ,37082   ,488,488,488
BEGIN DESCRIPTION:
Little Stink Creek 49.0
END DESCRIPTION:
XS GIS Cut Line= 3
      1422700.25      6852579.06      1423254.51       6852447.3
      1423604.98      6852088.02
#Sta/Elev= 30
  4430.3 2155.99  4609.9 2143.81  4620.2 2142.37  4627.4 2139.12  4648.9 2136.05
  4674.7 2128.19  4753.8  2124.6  4774.4 2131.42  4784.7 2128.05  4801.2 2125.78
  4806.4  2130.4  4843.4  2118.8  4848.5 2120.11  4856.6 2118.11  4897.7 2115.87
  4995.3 2114.55  4995.6 2114.05  5000.1 2114.55  5021.1 2115.41  5028.1 2119.92
  5035.2 2119.57  5042.2 2122.48  5056.4 2123.83    5106 2121.97  5120.1 2124.39
  5268.5 2128.58    5410 2138.68  5424.1 2142.99  5434.8 2143.96  5501.9 2149.92
#Mann= 5 ,-1 , 0
  4430.3     .07       0  4648.9     .16       0  4995.3     .07       0
  5000.1     .16       0  5434.8     .07       0
Bank Sta=4995.3,5000.1
XS Rating Curve= 0 ,0
Exp/Cntr=0.3,0.1

Type RM Length L Ch R = 1 ,36594   ,496,496,496
BEGIN DESCRIPTION:
Little Stink Creek 48.0
END DESCRIPTION:
XS GIS Cut Line= 3
      1423204.99        6853088.      1423560.63      6852796.57
      1423654.99      6852638.02
#Sta/Elev= 30
  4540.2 2166.42  4543.4 2166.42  4547.4 2163.05  4553.8 2162.46  4576.1 2155.32
  4617.8 2146.91  4664.9 2144.54  4668.7 2144.93  4689.5 2140.93  4824.6 2128.01
  4838.1 2125.71  4845.9 2119.67  4852.4  2120.8  4860.3 2117.03  4866.8 2118.26
  4895.5 2113.25  4909.8 2113.39  4916.3    2111    4945 2108.77  4952.9 2109.76
  4971.2 2107.12  4971.6 2106.62  4976.1 2107.12  4980.2 2108.77  5044.9 2109.45
  5054.1 2108.45  5096.9 2111.49  5126.3  2115.3  5139.7 2120.36  5184.5 2124.06
#Mann= 4 ,-1 , 0
  4540.2     .07       0  4664.9     .16       0  4971.2     .07       0
  4976.1     .16       0
Bank Sta=4971.2,4976.1
XS Rating Curve= 0 ,0
Exp/Cntr=0.3,0.1

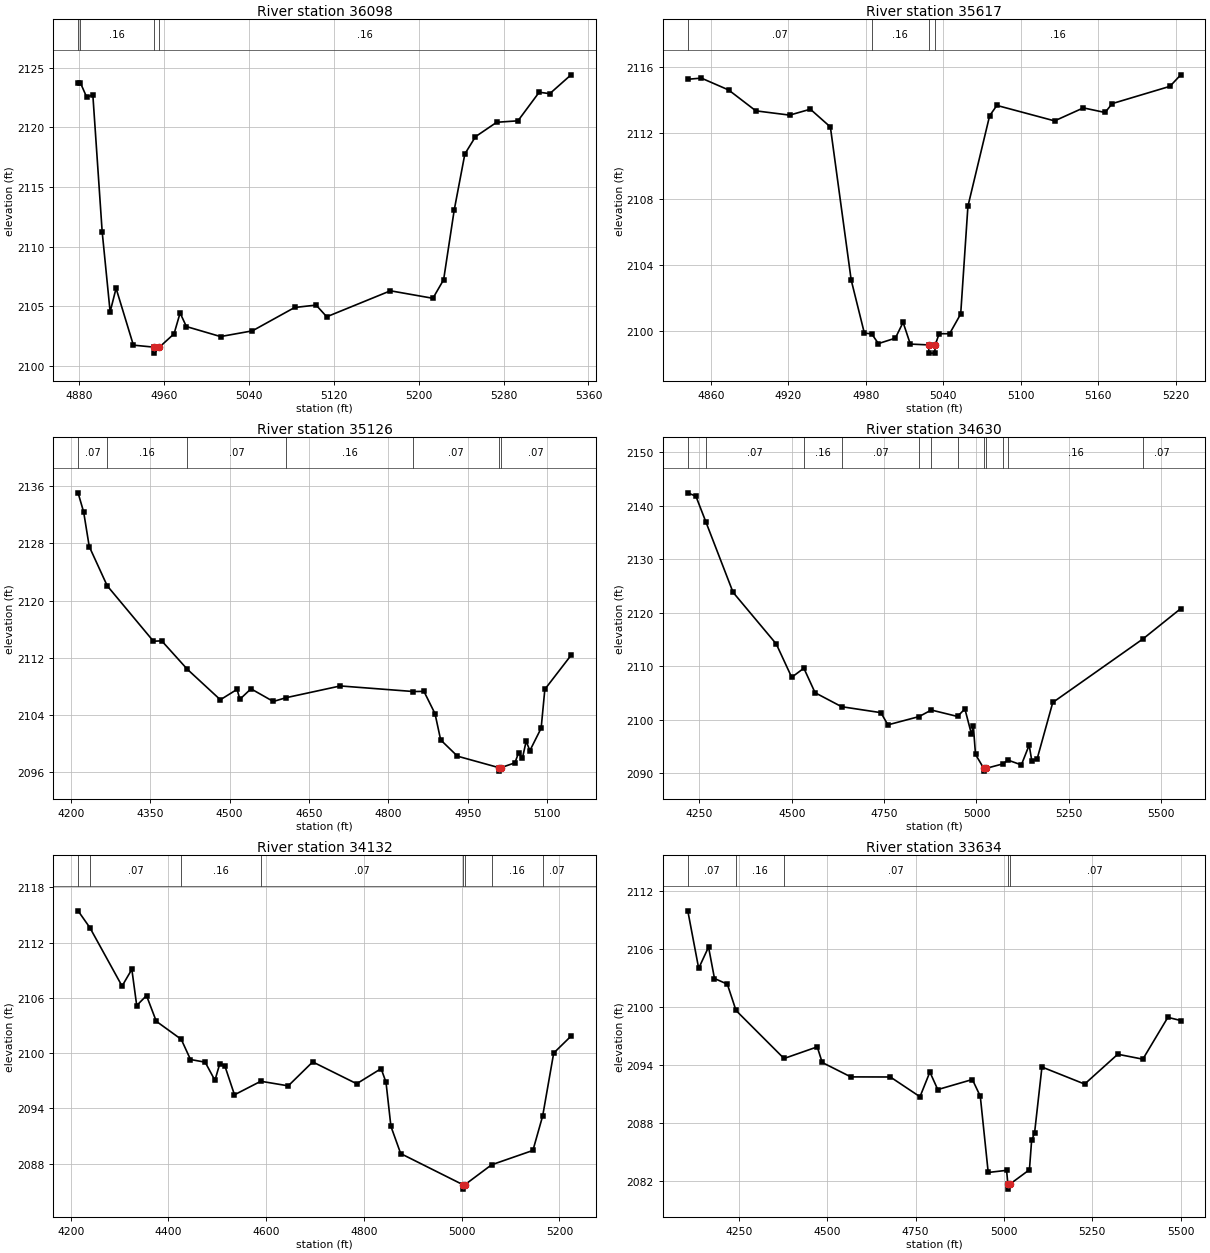
Type RM Length L Ch R = 1 ,36098   ,481,481,481
BEGIN DESCRIPTION:
Little Stink Creek 47.0
END DESCRIPTION:
XS GIS Cut Line= 3
      1423604.96      6853188.02      1423711.49      6853131.28
      1424055.03        6853138.
#Sta/Elev= 30
  4879.3 2123.76  4881.4 2123.76  4887.5 2122.52  4893.2 2122.75    4902 2111.25
  4909.5 2104.52  4915.1  2106.5  4931.4 2101.73  4950.8 2101.56  4951.2 2101.06
  4955.9 2101.56  4969.7 2102.68  4975.4 2104.43  4981.3 2103.29  5013.5 2102.45
  5043.5 2102.93  5083.3 2104.89  5103.5 2105.09  5113.5 2104.11  5173.5 2106.29
  5213.5 2105.66  5223.6 2107.22  5233.6 2113.08  5243.6 2117.77  5253.6 2119.22
  5273.6 2120.43  5293.6 2120.55  5313.6 2122.95  5323.6 2122.83  5343.6 2124.41
#Mann= 4 ,-1 , 0
  4879.3     .07       0  4881.4     .16       0  4950.8     .07       0
  4955.9     .16       0
Bank Sta=4950.8,4955.9
XS Rating Curve= 0 ,0
Exp/Cntr=0.3,0.1

Type RM Length L Ch R = 1 ,35617   ,491,491,491
BEGIN DESCRIPTION:
Little Stink Creek 46.0
END DESCRIPTION:
XS GIS Cut Line= 3
      1423655.02      6853488.01      1423804.64      6853538.15
        1423905.        6853338.
#Sta/Elev= 30
  4842.2 2115.28  4852.7 2115.35  4873.8 2114.63  4894.9 2113.36  4921.1  2113.1
  4937.1 2113.46  4952.6 2112.38  4968.7 2103.08  4978.9 2099.85  4984.6  2099.8
  4989.8 2099.21  5002.9 2099.54  5008.9  2100.5  5014.5 2099.18  5028.6 2099.13
    5029 2098.63  5033.4 2098.63  5033.8 2099.13  5036.8 2099.81  5044.9 2099.81
  5053.5 2101.01  5059.1 2107.56  5075.9 2113.06  5081.5 2113.69  5126.2 2112.75
  5148.5 2113.54  5165.3 2113.26  5170.8  2113.8  5215.5 2114.85  5223.9 2115.55
#Mann= 4 ,-1 , 0
  4842.2     .07       0  4984.6     .16       0  5028.6     .07       0
  5033.8     .16       0
Bank Sta=5028.6,5033.8
XS Rating Curve= 0 ,0
Exp/Cntr=0.3,0.1

Type RM Length L Ch R = 1 ,35126   ,496,496,496
BEGIN DESCRIPTION:
Little Stink Creek 45.0
END DESCRIPTION:
XS GIS Cut Line= 3
      1423404.97      6854088.01      1424151.15      6853839.42
      1424255.03      6853737.97
#Sta/Elev= 30
  4213.5 2135.07  4224.1 2132.38  4234.6 2127.57  4268.6 2122.08  4355.9 2114.34
  4371.6 2114.39    4420 2110.42  4482.4 2106.16    4514 2107.61  4519.3 2106.23
  4540.3 2107.69  4582.5 2105.92  4606.7 2106.45  4709.1 2108.09  4847.4 2107.31
  4867.2 2107.33  4888.1 2104.22  4898.8 2100.55  4930.5 2098.28  5008.2 2096.69
  5008.6 2096.19  5013.4 2096.69  5039.1 2097.35  5046.2 2098.77  5053.2 2097.96
  5060.4 2100.37  5067.4 2099.05  5088.7 2102.19  5095.7 2107.62  5145.2 2112.37
#Mann= 7 ,-1 , 0
  4213.5     .07       0  4268.6     .16       0    4420     .07       0
  4606.7     .16       0  4847.4     .07       0  5008.2     .07       0
  5013.4     .07       0
Bank Sta=5008.2,5013.4
XS Rating Curve= 0 ,0
Exp/Cntr=0.3,0.1

Type RM Length L Ch R = 1 ,34630   ,498,498,498
BEGIN DESCRIPTION:
Little Stink Creek 44.0
END DESCRIPTION:
XS GIS Cut Line= 3
      1423454.99        6854538.      1424205.09      6854319.78
      1424605.01      6853937.99
#Sta/Elev= 30
  4218.8 2142.41  4240.8 2141.77  4267.8 2136.97  4341.3 2123.83  4458.3 2114.18
    4500 2107.96  4532.9 2109.66  4563.3 2105.08  4635.1 2102.47  4741.3 2101.36
  4760.4 2099.08  4844.8 2100.63  4877.9 2101.85  4948.7 2100.65  4968.7 2102.06
  4986.4 2097.36  4991.6 2098.85  4997.4 2093.56  5019.9 2090.94  5020.3 2090.44
  5025.1 2090.94  5071.3 2091.79  5085.3  2092.5  5121.5  2091.6  5142.6  2095.3
  5149.8 2092.36    5164 2092.68  5206.5 2103.26  5450.6 2115.13  5552.9 2120.79
#Mann= 12 ,-1 , 0
  4218.8    .035       0  4267.8     .07       0  4532.9     .16       0
  4635.1     .07       0  4844.8     .16       0  4877.9     .07       0
  4948.7     .16       0  5019.9     .07       0  5025.1     .16       0
  5071.3     .07       0  5085.3     .16       0  5450.6     .07       0
Bank Sta=5019.9,5025.1
XS Rating Curve= 0 ,0
Exp/Cntr=0.3,0.1

Type RM Length L Ch R = 1 ,34132   ,498,498,498
BEGIN DESCRIPTION:
Little Stink Creek 43.0
END DESCRIPTION:
XS GIS Cut Line= 3
      1423704.98        6854688.      1424489.78      6854688.82
        1424655.        6854538.
#Sta/Elev= 30
  4215.2 2115.45  4239.4 2113.62  4305.2 2107.28  4325.2  2109.1  4335.2 2105.17
  4355.2 2106.25  4375.2 2103.46  4426.3  2101.5  4445.2 2099.31  4475.2 2099.02
  4495.2 2097.05  4505.2 2098.87  4515.2 2098.66  4535.2 2095.48    4589 2096.95
  4645.2 2096.45  4695.2 2099.05  4785.2 2096.68  4835.2 2098.32  4845.2 2096.83
  4855.2 2092.06  4875.2  2089.1  5001.8 2085.74  5002.2 2085.24  5007.1 2085.74
  5061.1 2087.88  5145.7 2089.44  5165.7 2093.19  5188.2 2100.01  5223.7 2101.85
#Mann= 8 ,-1 , 0
  4215.2     .16       0  4239.4     .07       0  4426.3     .16       0
    4589     .07       0  5001.8     .07       0  5007.1     .07       0
  5061.1     .16       0  5165.7     .07       0
Bank Sta=5001.8,5007.1
XS Rating Curve= 0 ,0
Exp/Cntr=0.3,0.1

Type RM Length L Ch R = 1 ,33634   ,377,377,377
BEGIN DESCRIPTION:
Little Stink Creek 42.0
END DESCRIPTION:
XS GIS Cut Line= 3
      1423804.98      6854737.99      1424604.92      6855138.03
      1424905.02      6854737.98
#Sta/Elev= 30
  4105.6 2109.92  4136.4 2103.98  4164.3 2106.18  4181.1 2102.93  4217.4 2102.35
    4242 2099.63  4377.8 2094.67  4471.8 2095.87  4485.8 2094.26  4566.8 2092.77
  4678.6 2092.76  4762.4 2090.72  4790.4 2093.27  4812.7 2091.46  4910.6  2092.5
    4933 2090.77  4955.4  2082.9  5007.4 2083.12    5011 2081.68  5011.4 2081.18
  5016.3 2081.68    5072 2083.18  5078.2 2086.21  5086.5 2086.97  5107.4 2093.79
  5228.2 2092.03  5321.9 2095.11  5392.8  2094.6  5463.6 2098.92  5500.1 2098.59
#Mann= 5 ,-1 , 0
  4105.6     .07       0    4242     .16       0  4377.8     .07       0
    5011     .07       0  5016.3     .07       0
Bank Sta=5011,5016.3
XS Rating Curve= 0 ,0
Exp/Cntr=0.3,0.1

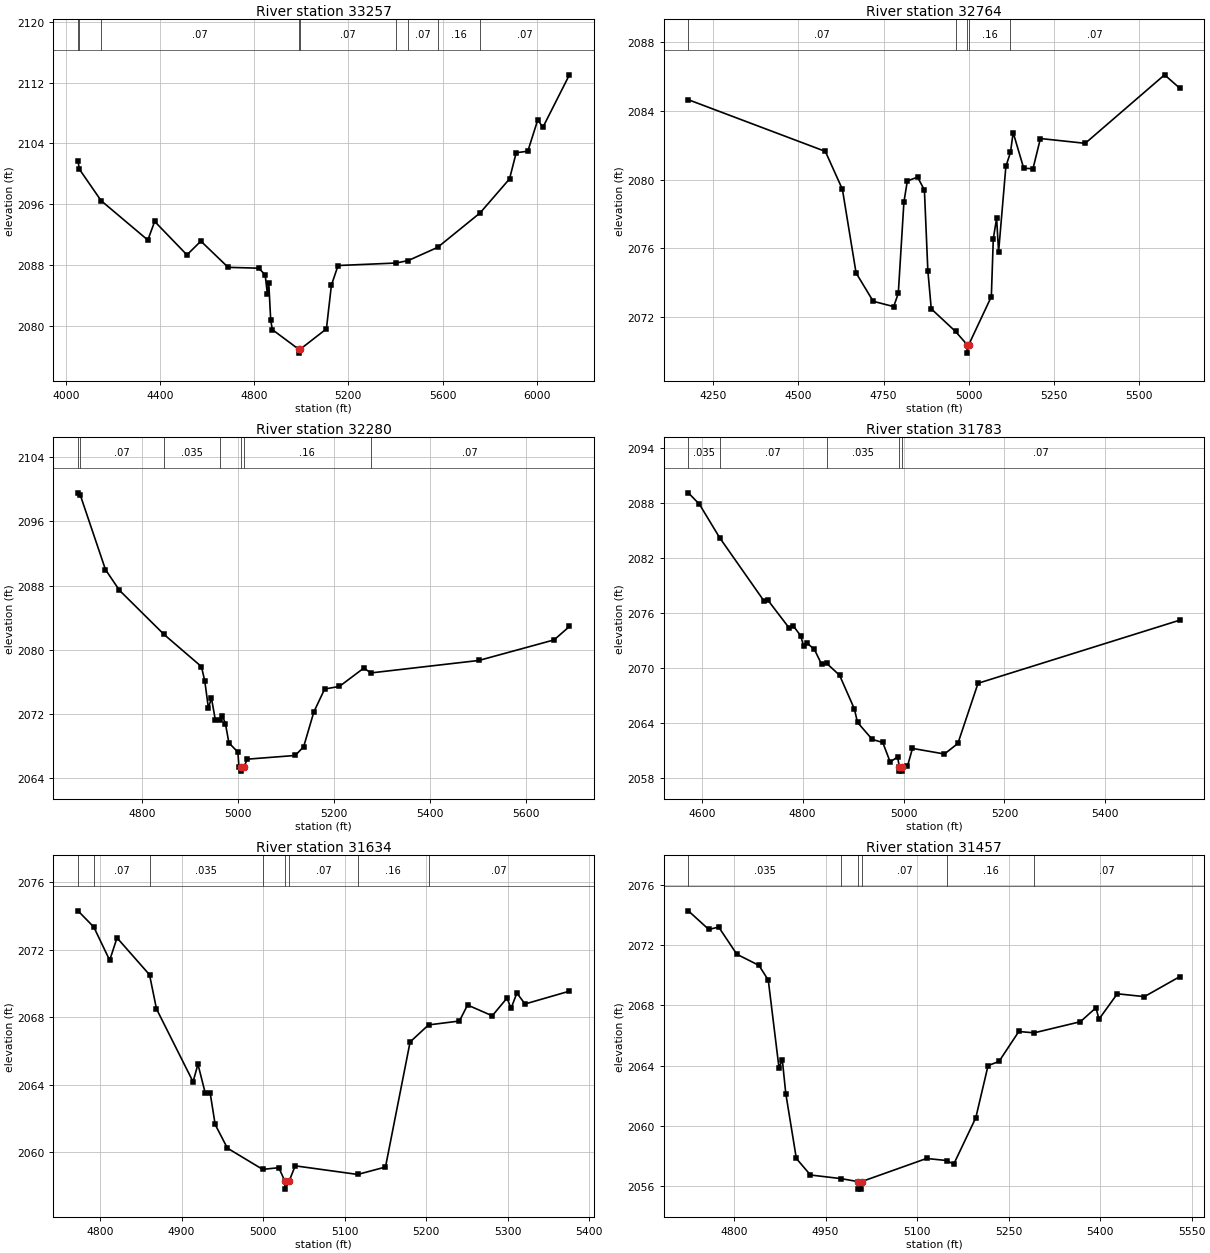
Type RM Length L Ch R = 1 ,33257   ,493,493,493
BEGIN DESCRIPTION:
Little Stink Creek 41.0
END DESCRIPTION:
XS GIS Cut Line= 3
      1423854.97      6854987.98      1424654.45      6855498.54
      1425454.97      6854688.03
#Sta/Elev= 30
  4051.4 2101.66  4057.3 2100.59  4149.5 2096.45  4348.1 2091.26  4377.2 2093.71
  4514.2 2089.31  4573.5 2091.12  4689.3 2087.67  4819.6 2087.56  4846.7 2086.67
    4856 2084.15  4861.9 2085.62  4870.1 2080.72  4877.1 2079.47  4989.6 2076.88
    4990 2076.38  4994.9 2076.88  5106.8 2079.57    5128 2085.33  5156.3 2087.91
  5402.6 2088.24  5454.1 2088.56  5579.2  2090.3  5759.5 2094.83  5884.7 2099.31
    5913 2102.75  5962.5 2102.96  6004.9 2107.11  6026.1 2106.08  6139.2 2113.01
#Mann= 9 ,-1 , 0
  4051.4     .07       0  4057.3     .16       0  4149.5     .07       0
  4989.6     .07       0  4994.9     .07       0  5402.6     .16       0
  5454.1     .07       0  5579.2     .16       0  5759.5     .07       0
Bank Sta=4989.6,4994.9
XS Rating Curve= 0 ,0
Exp/Cntr=0.3,0.1

Type RM Length L Ch R = 1 ,32764   ,484,484,484
BEGIN DESCRIPTION:
Little Stink Creek 40.0
END DESCRIPTION:
XS GIS Cut Line= 3
      1423914.04      6855977.09      1424734.62      6855918.07
      1425055.02      6855387.97
#Sta/Elev= 30
  4177.3 2084.66  4579.3 2081.65  4629.4 2079.44  4669.5 2074.57  4719.7 2072.92
  4779.8 2072.61  4793.4 2073.38  4809.9  2078.7  4819.9 2079.93    4850 2080.15
    4870  2079.4  4880.1 2074.71  4890.1 2072.48  4961.4 2071.16  4994.9  2070.4
  4995.3  2069.9  5000.4  2070.4  5066.4 2073.19  5072.2 2076.57  5081.9 2077.75
  5087.7  2075.8  5109.1 2080.78  5122.6 2081.59  5130.4 2082.75  5161.4 2080.67
  5188.6 2080.64  5210.4  2082.4  5341.9 2082.12  5574.8 2086.11  5619.4 2085.33
#Mann= 5 ,-1 , 0
  4177.3     .07       0  4961.4     .16       0  4994.9     .07       0
  5000.4     .16       0  5122.6     .07       0
Bank Sta=4994.9,5000.4
XS Rating Curve= 0 ,0
Exp/Cntr=0.3,0.1

Type RM Length L Ch R = 1 ,32280   ,497,497,497
BEGIN DESCRIPTION:
Little Stink Creek 39.0
END DESCRIPTION:
XS GIS Cut Line= 3
      1424654.97      6856538.02      1424919.91      6856336.62
        1425155.      6855688.01
#Sta/Elev= 30
  4667.2 2099.56  4671.7 2099.33  4724.4    2090  4753.5 2087.42  4846.2 2081.93
  4924.1 2077.92    4931 2076.15  4938.6 2072.77  4944.9 2074.01  4953.1 2071.26
  4962.4 2071.33  4967.7 2071.82    4974 2070.82  4981.3 2068.42    5000 2067.28
  5002.1 2065.46  5006.3 2065.41  5006.8 2064.91    5012 2065.41  5019.8  2066.4
  5119.3 2066.86  5136.8 2067.95  5158.1 2072.29  5180.5 2075.13  5211.3 2075.46
  5261.8 2077.73  5277.1 2077.14  5501.5 2078.69    5658 2081.25  5689.9 2082.92
#Mann= 7 ,-1 , 0
  4667.2    .035       0  4671.7     .07       0  4846.2    .035       0
  4962.4     .16       0  5006.3     .07       0    5012     .16       0
  5277.1     .07       0
Bank Sta=5006.3,5012
XS Rating Curve= 0 ,0
Exp/Cntr=0.3,0.1

Type RM Length L Ch R = 1 ,31783   ,149,149,149
BEGIN DESCRIPTION:
Little Stink Creek 38.0
END DESCRIPTION:
XS GIS Cut Line= 3
      1424955.02      6856887.98      1425299.15       6856635.7
        1425305.      6856088.03
#Sta/Elev= 30
  4573.3 2089.08  4595.3 2087.83  4635.4 2084.18  4722.7 2077.32  4731.1 2077.36
  4772.8 2074.35  4781.3 2074.56  4795.9 2073.49  4802.1 2072.32  4808.9 2072.66
    4823 2072.01  4837.6 2070.35  4847.9 2070.45  4873.2 2069.16  4902.5 2065.49
  4908.7 2064.02    4938 2062.16  4958.8 2061.83  4973.5 2059.69  4988.2 2060.26
  4991.5  2059.2  4991.9  2058.7  4996.7  2058.7  4997.2  2059.2  5007.7 2059.23
  5017.7 2061.18  5081.1 2060.57  5107.7 2061.72  5147.7 2068.29  5547.7 2075.18
#Mann= 5 ,-1 , 0
  4573.3    .035       0  4635.4     .07       0  4847.9    .035       0
  4991.5     .07       0  4997.2     .07       0
Bank Sta=4991.5,4997.2
XS Rating Curve= 0 ,0
Exp/Cntr=0.3,0.1

Type RM Length L Ch R = 1 ,31634   ,177,177,177
BEGIN DESCRIPTION:
Little Stink Creek 4432
END DESCRIPTION:
XS GIS Cut Line= 3
      1425184.71      6856882.59      1425374.03      6856757.16
      1425418.75      6856383.93
#Sta/Elev= 30
  4772.9  2074.3  4792.3 2073.34  4811.8 2071.37  4820.8  2072.7  4860.7 2070.51
  4869.2 2068.49  4914.1 2064.17  4920.1 2065.21  4929.1 2063.49  4935.1  2063.5
  4941.2 2061.64  4956.2 2060.24  4999.5 2058.98  5019.3 2059.08  5026.5 2058.31
    5027 2057.81  5032.2 2058.31  5039.4 2059.19  5116.1 2058.68  5150.2 2059.12
  5180.4 2066.53    5203 2067.54  5240.9 2067.77  5250.9 2068.72  5281.2 2068.08
  5299.3 2069.13  5304.3 2068.52  5311.4 2069.43  5321.4 2068.78  5375.9 2069.54
#Mann= 8 ,-1 , 0
  4772.9    .035       0  4792.3     .07       0  4860.7    .035       0
  4999.5     .07       0  5026.5     .07       0  5032.2     .07       0
  5116.1     .16       0    5203     .07       0
Bank Sta=5026.5,5032.2
XS Rating Curve= 0 ,0
Exp/Cntr=0.3,0.1

Type RM Length L Ch R = 1 ,31457   ,173,173,173
BEGIN DESCRIPTION:
Little Stink Creek 4431
END DESCRIPTION:
XS GIS Cut Line= 3
      1425249.82      6856997.08      1425499.66      6856882.66
      1425567.54      6856356.42
#Sta/Elev= 30
  4725.2  2074.3  4758.7 2073.06  4774.9 2073.22  4804.7 2071.41  4840.9 2070.67
  4856.2 2069.69  4873.7 2063.87  4879.2 2064.38  4884.9 2062.14  4902.2 2057.82
  4925.3 2056.72  4975.3 2056.48  5003.3 2056.28  5003.8 2055.78  5008.6 2055.78
  5009.1 2056.28  5115.6 2057.82  5149.4 2057.68    5160 2057.43  5196.3 2060.53
  5216.4    2064  5234.4 2064.28  5266.8 2066.27  5291.9 2066.18  5367.7 2066.92
  5393.2 2067.85  5398.2 2067.09  5428.2 2068.78  5472.6 2068.59  5530.6 2069.92
#Mann= 6 ,-1 , 0
  4725.2    .035       0  4975.3     .07       0  5003.3     .07       0
  5009.1     .07       0  5149.4     .16       0  5291.9     .07       0
Bank Sta=5003.3,5009.1
XS Rating Curve= 0 ,0
Exp/Cntr=0.3,0.1

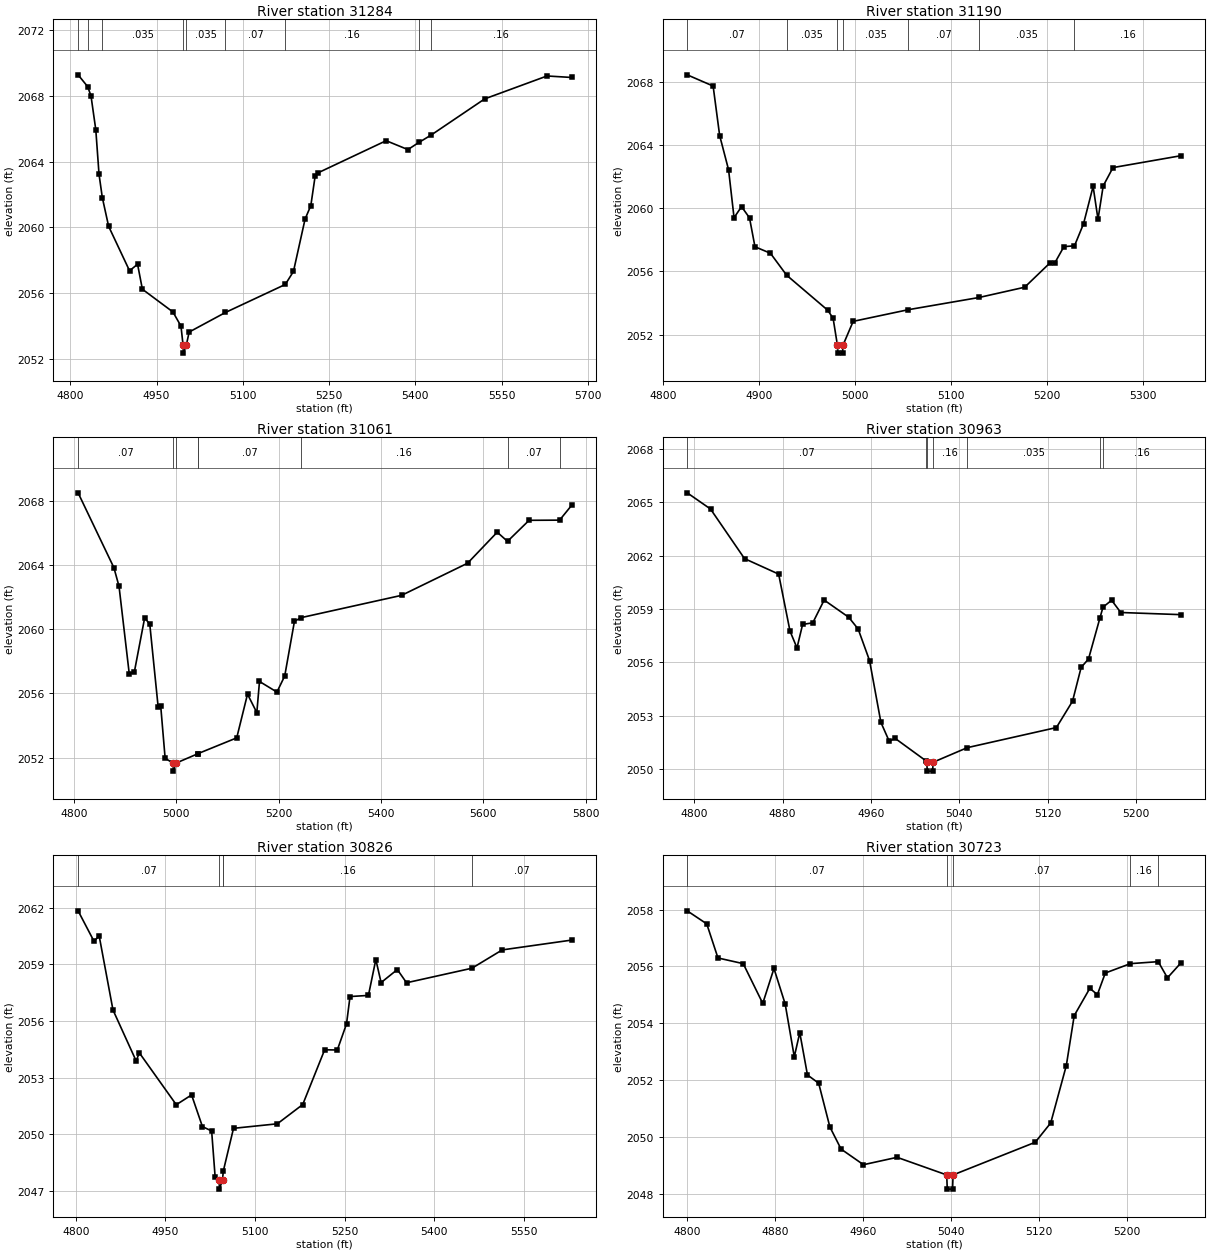
Type RM Length L Ch R = 1 ,31284   ,94,94,94
BEGIN DESCRIPTION:
Little Stink Creek 37.0
END DESCRIPTION:
XS GIS Cut Line= 3
      1425454.98      6857088.01       1425621.7      6857004.65
        1425705.      6856338.04
#Sta/Elev= 30
  4813.6 2069.27  4830.1 2068.56    4836    2068  4844.4 2065.93    4850 2063.23
  4855.7 2061.82  4866.7 2060.07  4903.1 2057.37    4917 2057.77  4925.4 2056.25
  4978.5 2054.87  4992.5 2054.01  4996.1 2052.87  4996.6 2052.37  5001.9 2052.87
  5006.7 2053.65  5069.9 2054.84  5173.9 2056.54  5188.1 2057.33  5208.3 2060.51
  5218.3 2061.33  5225.8 2063.12  5230.9 2063.32  5349.3 2065.27  5387.1 2064.73
  5406.5 2065.17  5427.4 2065.61  5520.7 2067.81    5629  2069.2  5671.8 2069.11
#Mann= 9 ,-1 , 0
  4813.6    .035       0  4830.1     .07       0  4855.7    .035       0
  4996.1    .035       0  5001.9    .035       0  5069.9     .07       0
  5173.9     .16       0  5406.5     .07       0  5427.4     .16       0
Bank Sta=4996.1,5001.9
XS Rating Curve= 0 ,0
Exp/Cntr=0.3,0.1

Type RM Length L Ch R = 1 ,31190   ,129,129,129
BEGIN DESCRIPTION:
Little Stink Creek 4430
END DESCRIPTION:
XS GIS Cut Line= 3
       1425535.4      6857155.51      1425688.36      6857071.32
      1425757.63      6856738.86
#Sta/Elev= 30
  4825.4 2068.44  4852.4 2067.73  4859.2  2064.6  4868.5 2062.43  4874.2  2059.4
    4882  2060.1  4890.3 2059.39    4896 2057.56  4912.1 2057.15    4929 2055.76
  4971.7 2053.55  4977.4 2053.04  4981.9 2051.33  4982.4 2050.83  4987.2 2050.83
  4987.7 2051.33  4998.3 2052.84  5055.9 2053.58  5129.4 2054.35    5177    2055
  5203.4 2056.54  5208.5 2056.55  5217.9 2057.57  5228.9 2057.62  5238.3 2059.01
  5248.3 2061.38  5253.4  2059.3  5258.8 2061.41    5269 2062.57  5339.6 2063.32
#Mann= 7 ,-1 , 0
  4825.4     .07       0    4929    .035       0  4981.9    .035       0
  4987.7    .035       0  5055.9     .07       0  5129.4    .035       0
  5228.9     .16       0
Bank Sta=4981.9,4987.7
XS Rating Curve= 0 ,0
Exp/Cntr=0.3,0.1

Type RM Length L Ch R = 1 ,31061   ,98,98,98
BEGIN DESCRIPTION:
Little Stink Creek 36.0
END DESCRIPTION:
XS GIS Cut Line= 3
        1425555.        6857188.      1425746.91      6857181.92
      1425955.01      6856437.98
#Sta/Elev= 30
    4808 2068.48    4878 2063.82    4888 2062.66    4908 2057.21  4918.1 2057.36
  4938.1  2060.7  4948.1  2060.3  4964.5 2055.14  4969.5  2055.2  4978.1 2051.96
  4993.6 2051.66  4994.1 2051.16  4999.4 2051.66  5041.9 2052.24  5042.4 2052.25
    5118 2053.23  5139.1 2055.95  5157.3  2054.8  5162.5 2056.74  5196.6 2056.08
  5211.8 2057.08  5230.8 2060.48  5243.6 2060.71  5440.2  2062.1  5569.2  2064.1
  5627.1 2066.03  5647.2 2065.46  5689.4 2066.77    5749 2066.78  5772.5  2067.7
#Mann= 8 ,-1 , 0
    4808     .07       0  4993.6     .07       0  4999.4     .07       0
  5041.9    .035       0  5042.4     .07       0  5243.6     .16       0
  5647.2     .07       0    5749     .16       0
Bank Sta=4993.6,4999.4
XS Rating Curve= 0 ,0
Exp/Cntr=0.3,0.1

Type RM Length L Ch R = 1 ,30963   ,137,137,137
BEGIN DESCRIPTION:
Little Stink Creek 4429
END DESCRIPTION:
XS GIS Cut Line= 3
      1425554.53      6857229.29      1425755.11      6857277.95
      1425900.02      6857086.02
#Sta/Elev= 30
  4793.6 2065.54  4814.7 2064.63  4845.5 2061.84  4876.4 2060.97  4886.7 2057.76
    4893 2056.82  4898.1 2058.14  4907.3 2058.23  4917.6 2059.51  4939.9 2058.54
  4948.4 2057.88  4958.7 2056.11    4969 2052.63  4976.6 2051.56  4981.7 2051.74
    5010 2050.46  5010.5 2050.39    5011 2049.89  5015.8 2049.89  5016.3 2050.39
  5047.2 2051.21  5127.9 2052.34  5142.5 2053.82  5150.3 2055.72    5157  2056.2
  5167.4 2058.52  5170.1 2059.11  5177.9  2059.5  5186.2 2058.81  5240.5 2058.69
#Mann= 7 ,-1 , 0
  4793.6     .07       0    5010     .16       0  5010.5     .07       0
  5016.3     .16       0  5047.2    .035       0  5167.4     .07       0
  5170.1     .16       0
Bank Sta=5010.5,5016.3
XS Rating Curve= 0 ,0
Exp/Cntr=0.3,0.1

Type RM Length L Ch R = 1 ,30826   ,103,103,103
BEGIN DESCRIPTION:
Little Stink Creek 35.1
END DESCRIPTION:
XS GIS Cut Line= 3
      1425569.93      6857350.16       1425754.9      6857415.32
      1426086.09      6856879.16
#Sta/Elev= 30
  4803.9 2061.84  4830.5 2060.23  4839.2 2060.51  4862.3 2056.59  4901.1 2053.89
  4906.4 2054.32  4968.3 2051.57  4993.9 2052.09  5012.1 2050.41  5027.5 2050.18
  5033.4 2047.72    5040  2047.6  5040.5  2047.1  5045.8  2047.6  5046.9 2048.04
  5064.1 2050.32  5137.5 2050.56    5180 2051.58  5216.7 2054.48  5237.9 2054.47
  5253.3 2055.85  5259.2  2057.3    5290 2057.36  5302.4 2059.26  5311.2 2058.04
  5338.4 2058.73  5353.8 2058.03  5463.3  2058.8    5514 2059.77  5630.2 2060.29
#Mann= 5 ,-1 , 0
  4803.9     .07       0    5040     .07       0  5045.8     .07       0
  5046.9     .16       0  5463.3     .07       0
Bank Sta=5040,5045.8
XS Rating Curve= 0 ,0
Exp/Cntr=0.3,0.1

Type RM Length L Ch R = 1 ,30723   ,161,161,161
BEGIN DESCRIPTION:
Little Stink Creek 4428
END DESCRIPTION:
XS GIS Cut Line= 3
       1425607.5      6857463.67      1425803.88       6857502.1
      1425983.36      6857329.08
#Sta/Elev= 30
  4799.9 2057.96  4817.7  2057.5  4827.9  2056.3  4850.9  2056.1  4868.7  2054.7
  4878.9 2055.93  4889.1 2054.68  4897.4 2052.82  4902.4 2053.67  4909.4 2052.18
  4919.6 2051.89  4929.8 2050.35    4940 2049.57  4960.4 2049.02    4991 2049.28
  5036.2 2048.66  5036.7 2048.16  5041.5 2048.16    5042 2048.66  5116.8 2049.81
  5130.9 2050.49  5145.1 2052.51  5152.3 2054.27  5166.5 2055.23  5173.4 2055.01
  5180.6 2055.77  5203.4  2056.1  5228.8 2056.17  5237.2  2055.6  5249.3 2056.12
#Mann= 5 ,-1 , 0
  4799.9     .07       0  5036.2     .07       0    5042     .07       0
  5203.4     .16       0  5228.8     .07       0
Bank Sta=5036.2,5042
XS Rating Curve= 0 ,0
Exp/Cntr=0.3,0.1