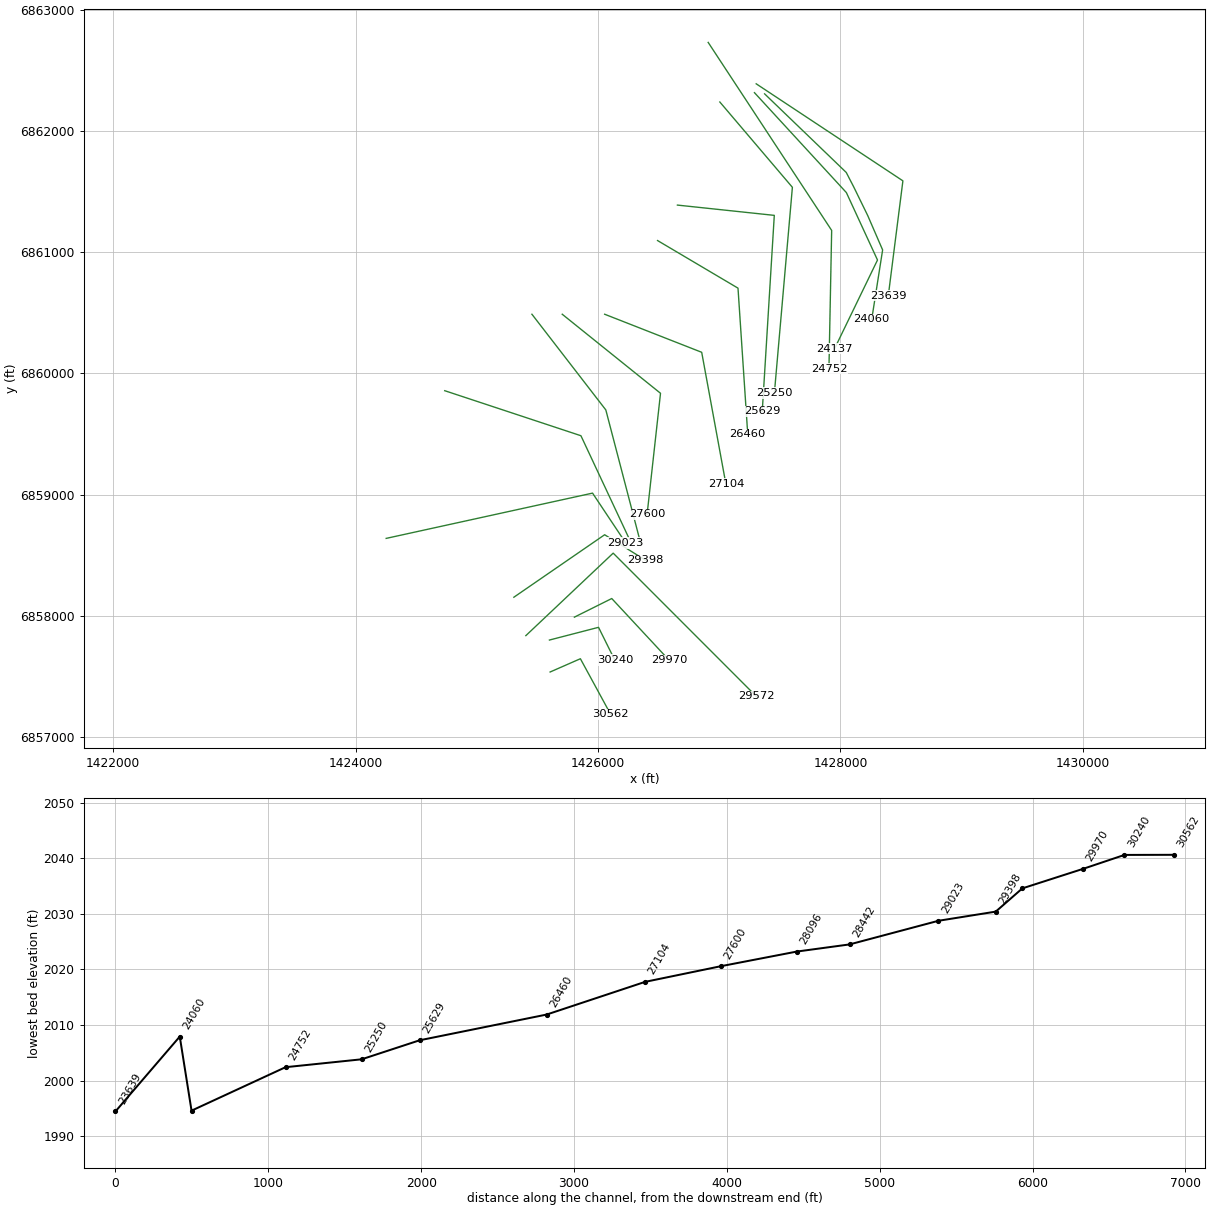
HEC-RAS study Little Stink Creek.prj: Little Stink Creek Base Level Engineering

--- Little Stink Creek.g01 (geometry) --- (continued)

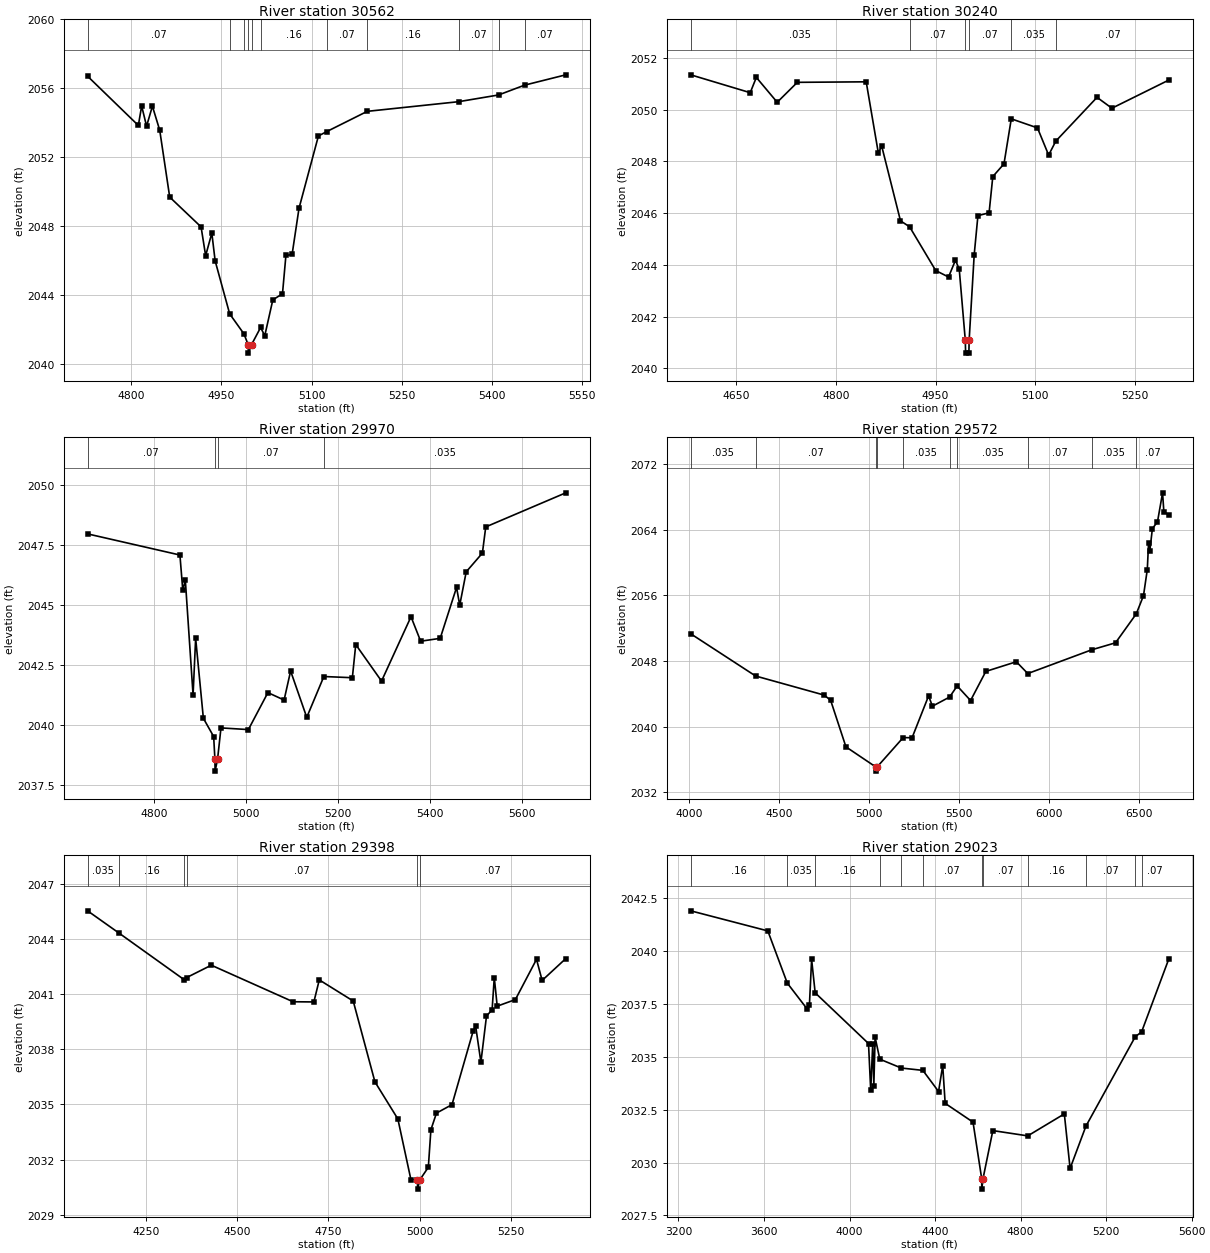
Type RM Length L Ch R = 1 ,30562   ,322,322,322
BEGIN DESCRIPTION:
Little Stink Creek 35.0
END DESCRIPTION:
XS GIS Cut Line= 3
      1425605.02      6857538.01      1425854.78       6857647.5
      1426104.99      6857188.01
#Sta/Elev= 30
  4727.3 2056.69  4811.8 2053.83  4817.3 2054.96  4825.5 2053.79  4835.2 2054.95
  4847.4 2053.55    4864 2049.67  4916.2 2047.94  4923.8 2046.27  4934.1 2047.58
  4939.6 2045.97  4963.8 2042.89  4987.5 2041.73  4994.5 2041.11  4994.9 2040.61
  5000.3 2041.11  5015.3  2042.1  5022.2 2041.62  5035.6  2043.7  5051.7 2044.06
  5057.4 2046.28  5067.7 2046.34  5079.2 2049.02  5111.5 2053.22  5125.1 2053.47
  5192.8 2054.65  5344.8 2055.21  5411.3  2055.6  5454.6 2056.17  5523.2 2056.77
#Mann= 11 ,-1 , 0
  4727.3     .07       0  4963.8     .16       0  4987.5     .07       0
  4994.5     .07       0  5000.3     .07       0  5015.3     .16       0
  5125.1     .07       0  5192.8     .16       0  5344.8     .07       0
  5411.3     .16       0  5454.6     .07       0
Bank Sta=4994.5,5000.3
XS Rating Curve= 0 ,0
Exp/Cntr=0.3,0.1

Type RM Length L Ch R = 1 ,30240   ,270,270,270
BEGIN DESCRIPTION:
Little Stink Creek 4103
END DESCRIPTION:
XS GIS Cut Line= 3
      1425599.46      6857801.58       1426004.4      6857906.43
      1426138.41      6857636.68
#Sta/Elev= 30
  4581.7 2051.34  4671.2 2050.65  4680.4 2051.24  4711.8 2050.28  4742.1 2051.05
  4845.7 2051.07  4863.9 2048.33  4869.1 2048.58  4897.3  2045.7    4911 2045.47
  4950.3 2043.78  4969.6 2043.53    4980 2044.18  4985.7 2043.83  4994.8 2041.09
  4995.3 2040.59  5000.2 2040.59  5000.6 2041.09  5008.2 2044.39  5013.8  2045.9
  5030.6 2046.01  5036.2 2047.41    5053  2047.9    5064 2049.64  5103.4 2049.29
  5120.2 2048.24    5131 2048.78    5193 2050.47  5215.4 2050.05  5301.2 2051.14
#Mann= 6 ,-1 , 0
  4581.7    .035       0    4911     .07       0  4994.8     .07       0
  5000.6     .07       0    5064    .035       0    5131     .07       0
Bank Sta=4994.8,5000.6
XS Rating Curve= 0 ,0
Exp/Cntr=0.3,0.1

Type RM Length L Ch R = 1 ,29970   ,398,398,398
BEGIN DESCRIPTION:
Little Stink Creek 4102
END DESCRIPTION:
XS GIS Cut Line= 3
      1425805.21      6857990.34      1426113.47      6858143.92
       1426587.5      6857634.43
#Sta/Elev= 30
  4655.6 2047.97  4856.5 2047.09  4862.7 2045.63  4868.3 2046.03  4885.1 2041.26
  4890.7 2043.62  4907.5 2040.29  4929.9 2039.53  4932.6 2038.59    4933 2038.09
  4938.4 2038.59  4945.8 2039.89  5005.4 2039.82  5047.9 2041.36  5083.1 2041.05
  5097.3 2042.26  5132.4 2040.33  5169.6 2042.03  5231.6 2041.98    5239 2043.36
  5295.1 2041.84  5359.2 2044.52  5380.2  2043.5  5422.7 2043.62  5458.3 2045.74
  5465.2    2045  5479.3 2046.39  5514.5 2047.17  5521.8 2048.26  5695.9 2049.68
#Mann= 4 ,-1 , 0
  4655.6     .07       0  4932.6     .07       0  4938.4     .07       0
  5169.6    .035       0
Bank Sta=4932.6,4938.4
XS Rating Curve= 0 ,0
Exp/Cntr=0.3,0.1

Type RM Length L Ch R = 1 ,29572   ,174,174,174
BEGIN DESCRIPTION:
Little Stink Creek 34.0
END DESCRIPTION:
XS GIS Cut Line= 3
      1425405.02      6857838.02      1426125.28      6858518.11
      1427305.03      6857337.97
#Sta/Elev= 30
  4009.4 2051.32  4370.2 2046.17  4752.1 2043.84  4787.5  2043.2  4872.5 2037.53
  5039.2 2035.07  5039.7 2034.57  5045.5 2035.07  5190.8 2038.66  5240.3 2038.64
  5332.2 2043.75  5353.4 2042.49  5448.7  2043.6  5491.2 2044.96  5565.6 2043.18
  5650.4 2046.73  5820.1 2047.91  5883.7 2046.47  6239.8 2049.37  6371.7 2050.22
  6487.3 2053.76  6527.2 2055.97  6548.4 2059.15  6555.5 2062.45  6562.6 2061.47
  6576.7 2064.15    6605 2064.97  6633.3 2068.51  6640.4 2066.23  6668.7 2065.78
#Mann= 10 ,-1 , 0
  4009.4    .035       0  4370.2     .07       0  5039.2     .07       0
  5045.5     .07       0  5190.8    .035       0  5448.7     .07       0
  5491.2    .035       0  5883.7     .07       0  6239.8    .035       0
  6487.3     .07       0
Bank Sta=5039.2,5045.5
XS Rating Curve= 0 ,0
Exp/Cntr=0.3,0.1

Type RM Length L Ch R = 1 ,29398   ,375,375,375
BEGIN DESCRIPTION:
Little Stink Creek 4112
END DESCRIPTION:
XS GIS Cut Line= 3
      1425305.96      6858154.55      1426054.86      6858669.76
      1426394.33      6858458.39
#Sta/Elev= 30
    4091 2045.54  4177.6 2044.32  4355.4 2041.79  4362.5 2041.91  4429.7 2042.58
  4653.5 2040.59  4710.4 2040.58  4725.2 2041.78  4818.1 2040.63  4877.5 2036.23
  4940.3 2034.21  4976.2 2030.89  4993.9 2030.89  4994.4 2030.39  5000.2 2030.89
  5023.7 2031.58  5030.7 2033.62    5046 2034.53  5088.5 2034.99  5146.3 2038.99
  5153.3 2039.25  5167.6  2037.3  5182.9 2039.81  5198.3 2040.16  5204.2 2041.91
  5212.2 2040.35    5262 2040.71  5319.8  2042.9  5335.2 2041.75  5399.9 2042.94
#Mann= 6 ,-1 , 0
    4091    .035       0  4177.6     .16       0  4355.4    .035       0
  4362.5     .07       0  4993.9     .07       0  5000.2     .07       0
Bank Sta=4993.9,5000.2
XS Rating Curve= 0 ,0
Exp/Cntr=0.3,0.1

Type RM Length L Ch R = 1 ,29023   ,581,581,581
BEGIN DESCRIPTION:
Little Stink Creek 4111
END DESCRIPTION:
XS GIS Cut Line= 3
      1424252.85      6858639.75      1425955.01        6859013.
      1426228.85      6858602.21
#Sta/Elev= 30
  3257.4 2041.91  3617.9 2040.96  3708.9 2038.49  3802.2 2037.26  3812.4 2037.45
  3822.7 2039.61  3839.3 2038.03  4088.8 2035.63  4099.1 2033.41  4108.6 2035.63
  4113.7 2033.64  4119.6 2035.93  4141.5 2034.89  4242.2 2034.47  4342.9 2034.36
  4416.4 2033.36  4435.8 2034.59  4447.2  2032.8  4577.5 2031.91    4618 2029.24
  4618.5 2028.74  4624.3 2029.24  4670.2 2031.51  4833.5 2031.26  5004.5  2032.3
  5031.5 2029.72  5105.5 2031.72  5336.1 2035.95  5365.8 2036.18  5493.7 2039.65
#Mann= 12 ,-1 , 0
  3257.4     .16       0  3708.9    .035       0  3839.3     .16       0
  4141.5     .07       0  4242.2     .16       0  4342.9     .07       0
    4618     .07       0  4624.3     .07       0  4833.5     .16       0
  5105.5     .07       0  5336.1     .16       0  5365.8     .07       0
Bank Sta=4618,4624.3
XS Rating Curve= 0 ,0
Exp/Cntr=0.3,0.1

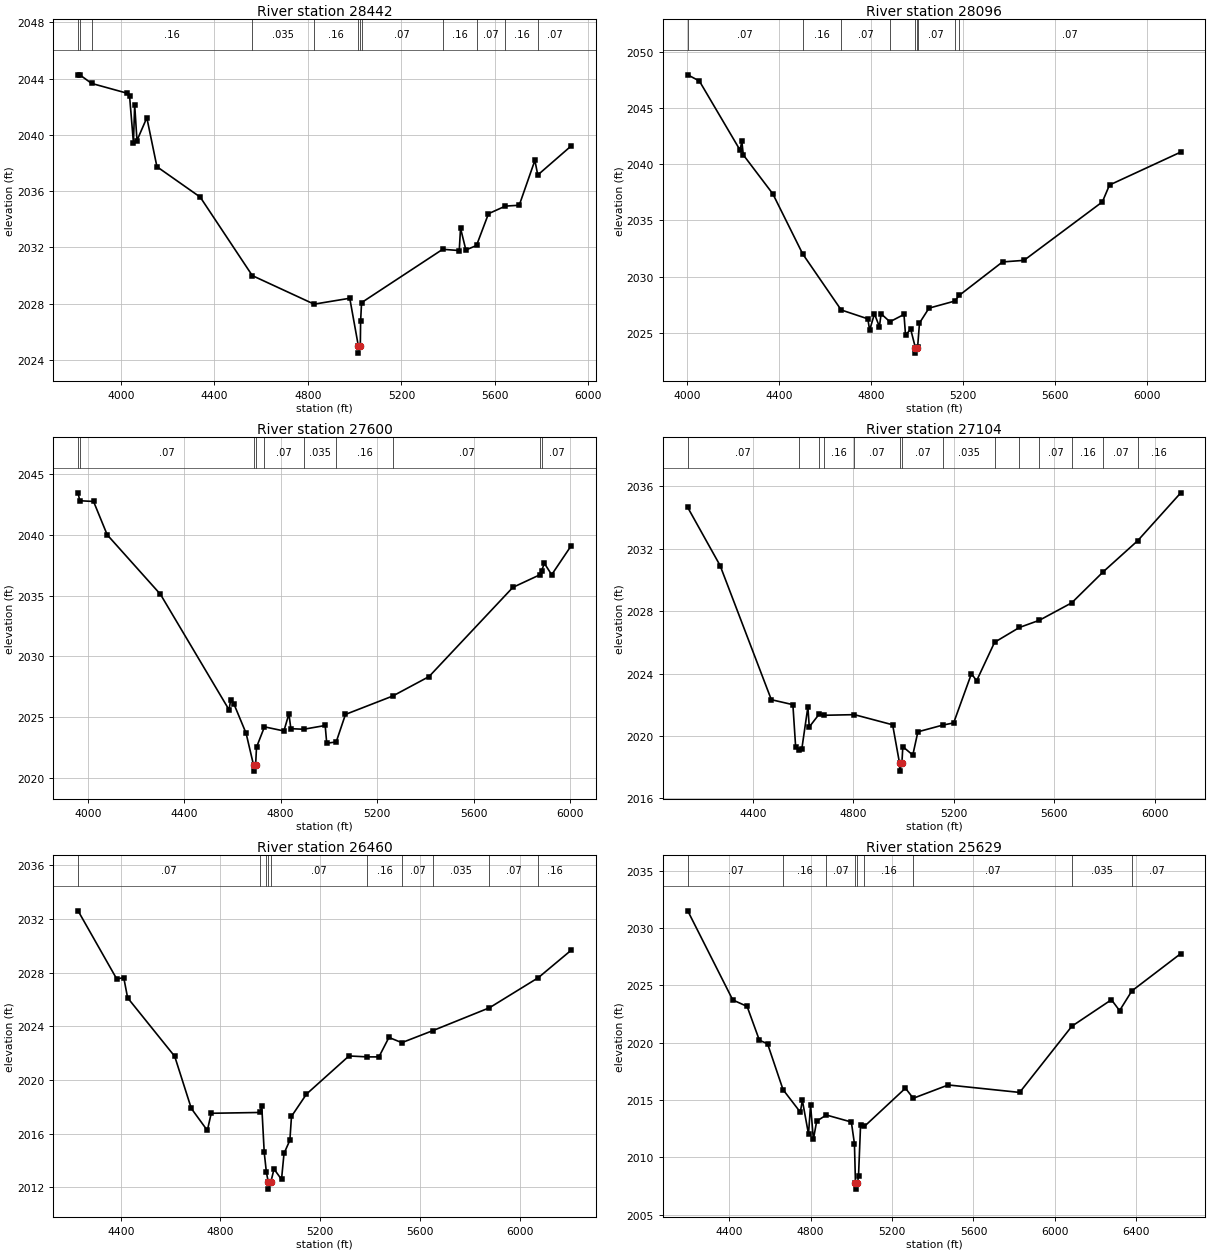
Type RM Length L Ch R = 1 ,28442   ,346,346,346
BEGIN DESCRIPTION:
Little Stink Creek 4110
END DESCRIPTION:
XS GIS Cut Line= 3
      1424735.68      6859857.56      1425859.22      6859486.25
      1426252.19      6858647.77
#Sta/Elev= 30
  3816.7 2044.26    3824 2044.27  3874.5 2043.66  4027.2 2042.96  4037.2 2042.73
  4053.6 2039.44  4058.9 2042.14  4068.7  2039.6  4110.9 2041.22  4154.1 2037.74
  4339.2 2035.58  4562.1    2030  4826.5 2027.97  4979.1 2028.39  5015.9 2024.99
  5016.4 2024.49  5024.2 2024.99  5025.5 2026.76  5029.6 2028.08  5376.7 2031.87
  5447.5 2031.78    5453 2033.37  5475.8 2031.82  5521.3 2032.14  5572.6  2034.4
  5644.8 2034.94  5704.1    2035  5771.1 2038.19  5783.4 2037.15    5926 2039.21
#Mann= 12 ,-1 , 0
  3816.7     .16       0    3824     .07       0  3874.5     .16       0
  4562.1    .035       0  4826.5     .16       0  5015.9     .07       0
  5024.2     .16       0  5029.6     .07       0  5376.7     .16       0
  5521.3     .07       0  5644.8     .16       0  5783.4     .07       0
Bank Sta=5015.9,5024.2
XS Rating Curve= 0 ,0
Exp/Cntr=0.3,0.1

Type RM Length L Ch R = 1 ,28096   ,496,496,496
BEGIN DESCRIPTION:
Little Stink Creek 33.0
END DESCRIPTION:
XS GIS Cut Line= 3
      1425454.98      6860488.03      1426064.63       6859698.9
        1426355.      6858588.02
#Sta/Elev= 30
  4002.8 2047.95  4053.4  2047.4  4230.3 2041.26  4238.3 2042.03  4244.6 2040.83
  4373.2 2037.36  4503.1 2032.02  4670.5 2027.04  4786.3 2026.25  4794.4 2025.24
  4815.2  2026.7  4836.9 2025.55  4844.2  2026.7  4882.5 2025.99  4943.8 2026.64
  4950.6 2024.79  4972.8 2025.34  4993.1  2023.7  4993.6  2023.2  5001.7  2023.7
  5003.1 2023.73  5011.3 2025.88  5052.6  2027.2  5164.7 2027.83  5184.4 2028.34
  5372.5 2031.31    5466 2031.45    5807 2036.65  5838.1 2038.15  6148.2 2041.08
#Mann= 9 ,-1 , 0
  4002.8     .07       0  4503.1     .16       0  4670.5     .07       0
  4882.5    .035       0  4993.1    .035       0  5001.7    .035       0
  5003.1     .07       0  5164.7     .16       0  5184.4     .07       0
Bank Sta=4993.1,5001.7
XS Rating Curve= 0 ,0
Exp/Cntr=0.3,0.1

Type RM Length L Ch R = 1 ,27600   ,496,496,496
BEGIN DESCRIPTION:
Little Stink Creek 32.0
END DESCRIPTION:
XS GIS Cut Line= 3
      1425704.99      6860488.01      1426515.71      6859836.28
        1426405.        6858838.
#Sta/Elev= 30
  3959.8 2043.44  3966.7 2042.79    4024 2042.73  4080.6 2039.99  4301.4  2035.1
  4586.2  2025.6  4592.6 2026.44    4607 2026.05  4656.6 2023.68  4687.5 2021.07
    4688 2020.57  4696.1 2021.07  4699.8 2022.53  4732.8 2024.21  4813.4 2023.87
  4834.2 2025.28  4842.2 2024.06  4895.2 2024.01  4984.6 2024.32    4991 2022.86
  5030.3 2022.97  5068.7 2025.23  5264.6 2026.74  5415.3 2028.34  5762.9 2035.67
  5875.5 2036.71    5882 2037.05  5893.7 2037.64  5923.9 2036.71  6004.4 2039.08
#Mann= 10 ,-1 , 0
  3959.8     .16       0  3966.7     .07       0  4687.5    .035       0
  4696.1     .07       0  4732.8     .07       0  4895.2    .035       0
  5030.3     .16       0  5264.6     .07       0  5875.5     .16       0
    5882     .07       0
Bank Sta=4687.5,4696.1
XS Rating Curve= 0 ,0
Exp/Cntr=0.3,0.1

Type RM Length L Ch R = 1 ,27104   ,644,644,644
BEGIN DESCRIPTION:
Little Stink Creek 31.0
END DESCRIPTION:
XS GIS Cut Line= 3
      1426054.98      6860488.01      1426855.45      6860174.18
      1427055.01      6859087.95
#Sta/Elev= 30
  4140.2 2034.65  4269.1 2030.93  4473.2 2022.33  4559.1 2022.01  4570.1  2019.3
  4581.9 2019.12  4594.5 2019.15  4618.9 2021.87  4624.3 2020.58  4664.6 2021.42
  4682.3 2021.33  4804.2 2021.37  4956.5 2020.72  4984.1 2018.25  4984.6 2017.75
  4993.4 2018.25  4997.1 2019.32  5036.8 2018.78  5057.1 2020.27  5156.1  2020.7
  5199.5 2020.84  5270.6    2024    5291 2023.54  5362.7 2026.01  5461.7 2026.96
  5541.1 2027.42  5670.1 2028.54  5795.6 2030.53  5932.8 2032.52  6104.4 2035.59
#Mann= 14 ,-1 , 0
  4140.2     .07       0  4581.9     .16       0  4664.6     .07       0
  4682.3     .16       0  4804.2     .07       0  4984.1     .07       0
  4993.4     .07       0  5156.1    .035       0  5362.7     .07       0
  5461.7     .16       0  5541.1     .07       0  5670.1     .16       0
  5795.6     .07       0  5932.8     .16       0
Bank Sta=4984.1,4993.4
XS Rating Curve= 0 ,0
Exp/Cntr=0.3,0.1

Type RM Length L Ch R = 1 ,26460   ,831,831,831
BEGIN DESCRIPTION:
Little Stink Creek 30.1
END DESCRIPTION:
XS GIS Cut Line= 3
       1426491.3      6861095.64      1427154.87      6860703.06
      1427235.19      6859498.83
#Sta/Elev= 30
    4229  2032.6  4384.3 2027.52  4412.2 2027.63  4427.8 2026.12  4616.7 2021.76
  4683.3 2017.88  4747.6 2016.24  4763.2 2017.52  4958.9 2017.58    4966 2018.03
  4975.8 2014.61  4984.4 2013.14  4992.3 2012.37  4992.8 2011.87    5002 2012.37
  5015.1 2013.37  5045.2 2012.59  5055.2 2014.53  5078.7 2015.51  5085.2 2017.29
  5145.4 2018.95  5315.8 2021.79  5389.7 2021.72    5436 2021.72  5476.1 2023.17
  5527.8 2022.78  5652.7 2023.68  5879.5 2025.38  6075.4 2027.62  6206.9 2029.66
#Mann= 10 ,-1 , 0
    4229     .07       0  4958.9     .16       0  4984.4     .07       0
  4992.3     .07       0    5002     .07       0  5389.7     .16       0
  5527.8     .07       0  5652.7    .035       0  5879.5     .07       0
  6075.4     .16       0
Bank Sta=4992.3,5002
XS Rating Curve= 0 ,0
Exp/Cntr=0.3,0.1

Type RM Length L Ch R = 1 ,25629   ,379,379,379
BEGIN DESCRIPTION:
Little Stink Creek 30.0
END DESCRIPTION:
XS GIS Cut Line= 3
      1426655.04        6861388.      1427454.25       6861303.2
        1427355.      6859688.04
#Sta/Elev= 30
  4196.3  2031.5  4417.5 2023.73  4487.9 2023.17  4548.2 2020.22  4588.4 2019.91
  4664.5 2015.91  4749.3 2013.95  4759.4 2014.98  4789.6 2012.03  4799.6 2014.57
  4813.5 2011.58  4829.8 2013.17  4877.3  2013.7    5000 2013.09  5015.2  2011.2
  5020.3 2007.74  5020.8 2007.24  5030.1 2007.74  5035.3 2008.42  5045.3 2012.82
  5064.3 2012.71  5265.7 2016.04  5304.1 2015.16  5476.1 2016.32  5826.8 2015.67
  6083.2 2021.44  6277.6 2023.75  6317.7  2022.8    6378 2024.52  6618.2 2027.77
#Mann= 9 ,-1 , 0
  4196.3     .07       0  4664.5     .16       0  4877.3     .07       0
  5020.3     .07       0  5030.1     .07       0  5064.3     .16       0
  5304.1     .07       0  6083.2    .035       0    6378     .07       0
Bank Sta=5020.3,5030.1
XS Rating Curve= 0 ,0
Exp/Cntr=0.3,0.1

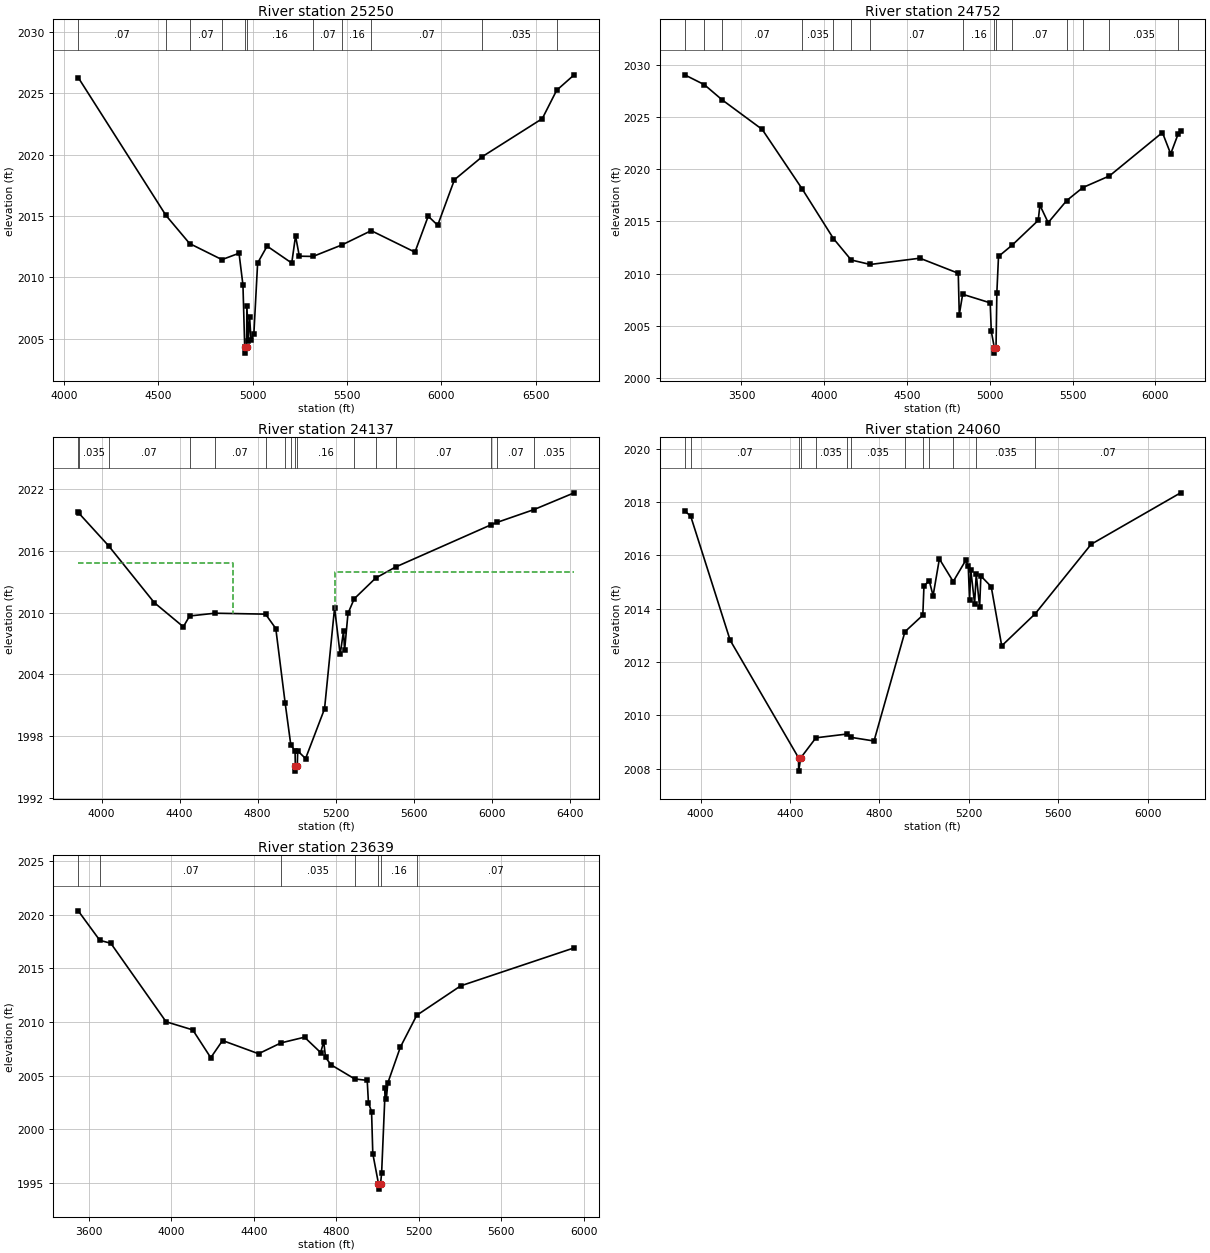
Type RM Length L Ch R = 1 ,25250   ,498,498,498
BEGIN DESCRIPTION:
Little Stink Creek 29.0
END DESCRIPTION:
XS GIS Cut Line= 3
      1427005.01      6862237.99      1427603.51      6861534.55
        1427455.      6859838.04
#Sta/Elev= 30
  4076.4 2026.28  4540.8 2015.05  4666.4 2012.75  4837.6 2011.44  4928.1 2011.96
  4948.9 2009.37  4958.2 2004.32  4958.7 2003.82  4968.1 2004.32  4969.7 2007.69
  4977.5 2004.84    4984 2006.78  4991.7 2004.92  5006.6 2005.37  5026.6 2011.16
  5076.8 2012.54  5207.3 2011.16  5227.4 2013.37  5247.5 2011.72    5320  2011.7
  5474.8 2012.65  5628.2  2013.8  5859.8 2012.05  5930.1 2014.98  5980.3 2014.24
    6069 2017.95  6216.2 2019.83  6534.2 2022.93  6610.4 2025.24    6703  2026.5
#Mann= 11 ,-1 , 0
  4076.4     .07       0  4540.8    .035       0  4666.4     .07       0
  4837.6     .16       0  4958.2     .07       0  4968.1     .16       0
    5320     .07       0  5474.8     .16       0  5628.2     .07       0
  6216.2    .035       0  6610.4     .07       0
Bank Sta=4958.2,4968.1
XS Rating Curve= 0 ,0
Exp/Cntr=0.3,0.1

Type RM Length L Ch R = 1 ,24752   ,615,615,615
BEGIN DESCRIPTION:
Little Stink Creek 28.0
END DESCRIPTION:
XS GIS Cut Line= 3
      1426908.96      6862729.26       1427927.5      6861179.19
        1427905.      6860037.97
#Sta/Elev= 30
  3156.8 2029.02  3275.3 2028.08  3382.8 2026.63    3625  2023.8  3866.9  2018.1
  4055.4 2013.36  4162.7 2011.31  4277.8 2010.88  4577.7 2011.48  4809.6 2010.04
  4815.7 2006.07  4836.1 2008.03  5002.5 2007.21  5009.3 2004.48  5027.8  2002.9
  5028.3  2002.4  5037.8  2002.9  5042.8 2008.18  5052.8 2011.65    5136 2012.74
  5292.8  2015.1  5302.8 2016.56  5352.8 2014.88  5464.6 2016.99  5562.6 2018.24
    5723 2019.35    6043  2023.5    6093 2021.46  6138.7 2023.39    6153 2023.68
#Mann= 15 ,-1 , 0
  3156.8     .07       0  3275.3     .16       0  3382.8     .07       0
  3866.9    .035       0  4055.4     .07       0  4162.7    .035       0
  4277.8     .07       0  4836.1     .16       0  5027.8     .07       0
  5037.8     .16       0    5136     .07       0  5464.6    .035       0
  5562.6     .07       0    5723    .035       0  6138.7     .07       0
Bank Sta=5027.8,5037.8
XS Rating Curve= 0 ,0
Exp/Cntr=0.3,0.1

Type RM Length L Ch R = 1 ,24137   ,77,77,77
BEGIN DESCRIPTION:
Little Stink Creek 27.0
END DESCRIPTION:
XS GIS Cut Line= 4
      1427290.67      6862314.91       1428048.8      6861491.05
      1428305.53      6860934.97      1427951.94      6860205.21
#Sta/Elev= 30
  3880.4 2019.76  3885.2 2019.64  4036.1  2016.5  4270.3 2010.97  4419.4 2008.62
  4451.7 2009.67  4581.4 2009.94    4841 2009.85  4893.5 2008.45  4941.4 2001.22
  4970.8 1997.09  4992.2 1996.58  4993.7 1995.08  4994.2 1994.58  5003.7 1995.08
  5005.9 1996.55  5046.2  1995.8  5143.5 2000.64  5194.9 2010.46  5223.6 2005.93
  5240.8  2008.2  5246.3 2006.33  5263.7 2009.92  5295.5 2011.34  5405.7 2013.36
  5508.5 2014.44  5997.2 2018.54  6028.9 2018.78  6217.4 2020.02  6423.4 2021.65
#Mann= 16 ,-1 , 0
  3880.4     .07       0  3885.2    .035       0  4036.1     .07       0
  4451.7    .035       0  4581.4     .07       0    4841     .16       0
  4941.4     .07       0  4970.8     .16       0  4993.7     .07       0
  5003.7     .16       0  5295.5     .07       0  5405.7    .035       0
  5508.5     .07       0  5997.2    .035       0  6028.9     .07       0
  6217.4    .035       0
#XS Ineff= 2 , 0
         4672.59 2014.85 5196.45         2013.98
Permanent Ineff=
       F       F
Bank Sta=4993.7,5003.7
XS Rating Curve= 0 ,0
Exp/Cntr=0.3,0.1

Type RM Length L Ch R = 1 ,24060   ,421,421,421
BEGIN DESCRIPTION:
Little Stink Creek 4280
END DESCRIPTION:
XS GIS Cut Line= 6
      1427374.36      6862305.06      1428047.75      6861657.09
      1428110.49      6861535.66      1428224.95      6861301.52
      1428347.79      6861018.22      1428258.02      6860446.63
#Sta/Elev= 30
  3928.8 2017.67  3955.5 2017.48  4132.3 2012.82  4438.3 2008.41  4438.8 2007.91
  4448.3 2008.41  4516.1 2009.16  4653.4  2009.3  4670.9 2009.18    4776 2009.04
  4914.5 2013.14  4994.4 2013.76  4999.5 2014.85  5022.9 2015.06  5040.4 2014.49
  5068.5 2015.87  5130.4 2015.02  5186.6 2015.82  5197.7  2015.6  5203.6 2014.32
  5209.1 2015.45  5226.1 2014.19  5233.5 2015.29  5248.6 2014.07  5254.2 2015.23
  5300.5 2014.83  5347.5 2012.61  5496.9 2013.81  5747.6 2016.42    6148 2018.35
#Mann= 13 ,-1 , 0
  3928.8    .035       0  3955.5     .07       0  4438.3    .035       0
  4448.3     .07       0  4516.1    .035       0  4653.4     .07       0
  4670.9    .035       0  4914.5     .07       0  4994.4    .035       0
  5022.9     .07       0  5130.4     .16       0  5233.5    .035       0
  5496.9     .07       0
Bank Sta=4438.3,4448.3
XS Rating Curve= 0 ,0
Exp/Cntr=0.3,0.1

Type RM Length L Ch R = 1 ,23639   ,675,675,675
BEGIN DESCRIPTION:
Little Stink Creek 26.0
END DESCRIPTION:
XS GIS Cut Line= 3
      1427305.04      6862387.97      1428515.05      6861587.89
      1428394.75      6860642.21
#Sta/Elev= 30
  3549.4 2020.35  3654.1  2017.6  3707.3 2017.33  3975.2 2010.02  4104.6 2009.26
  4191.9 2006.67    4249 2008.27  4423.6 2007.04  4532.3 2008.05  4646.3 2008.58
  4724.5 2007.15  4739.6 2008.17  4748.2 2006.69  4775.7    2006  4889.8 2004.69
  4950.2 2004.56  4956.2 2002.48  4971.3 2001.65  4977.3 1997.74  5004.9 1994.93
  5005.4 1994.43    5015 1994.93  5020.1 1995.94  5037.6 2003.84  5042.6 2002.78
  5050.3 2004.33  5110.8 2007.65  5190.3 2010.62  5403.1 2013.36  5953.3  2016.9
#Mann= 7 ,-1 , 0
  3549.4    .035       0  3654.1     .07       0  4532.3    .035       0
  4889.8     .16       0  5004.9     .07       0    5015     .16       0
  5190.3     .07       0
Bank Sta=5004.9,5015
XS Rating Curve= 0 ,0
Exp/Cntr=0.3,0.1