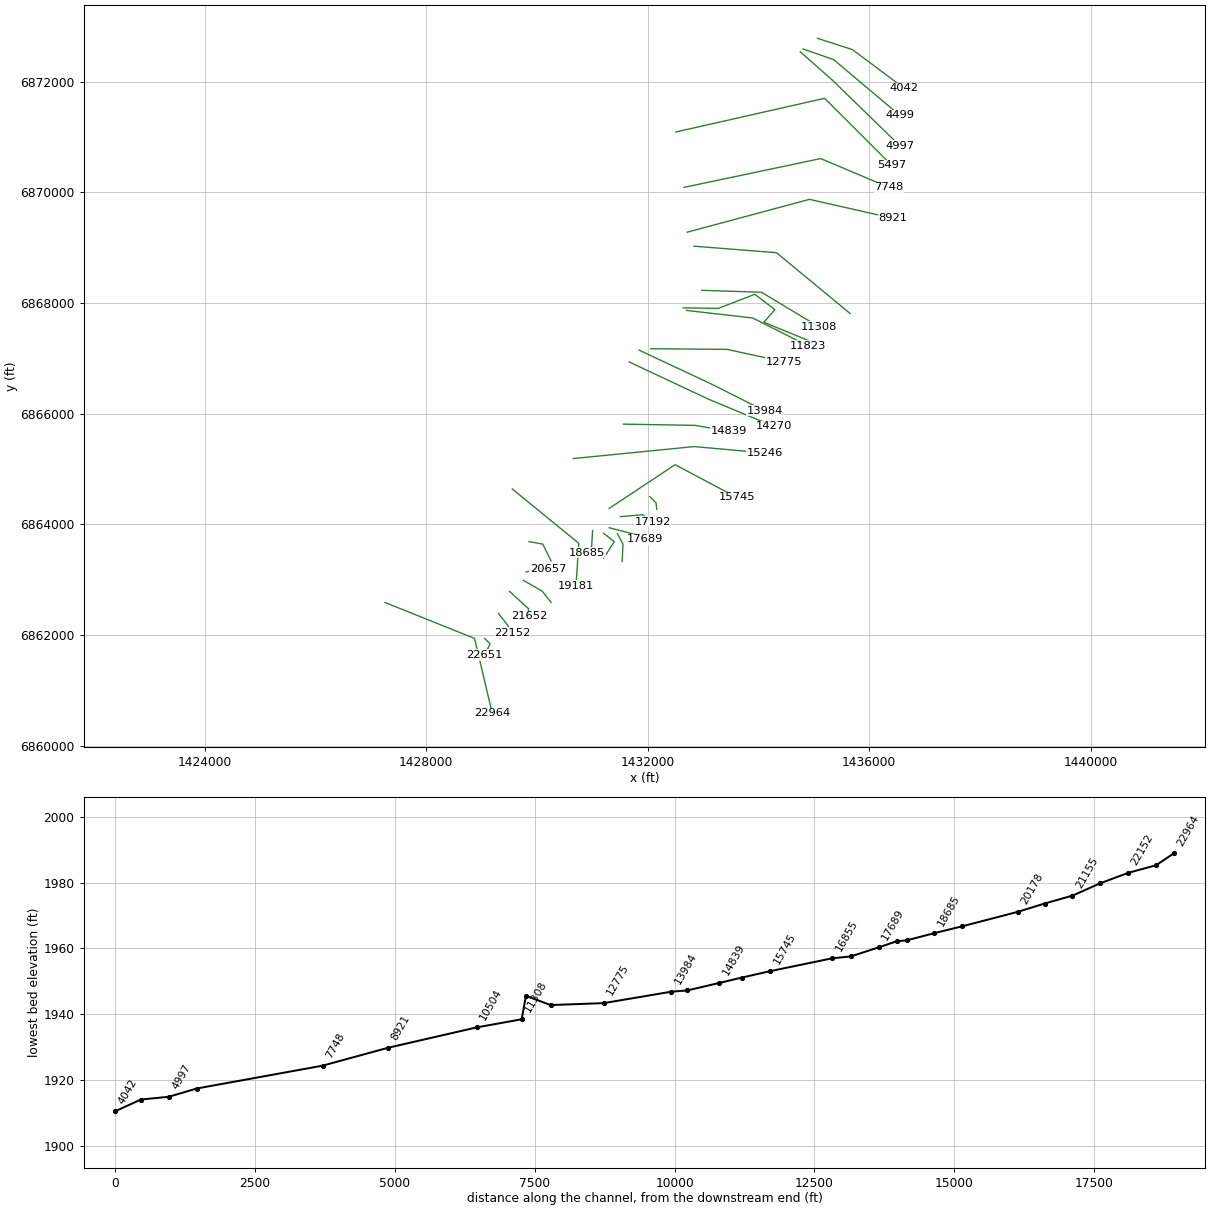
HEC-RAS study Little Stink Creek.prj: Little Stink Creek Base Level Engineering

--- Little Stink Creek.g01 (geometry) --- (continued)

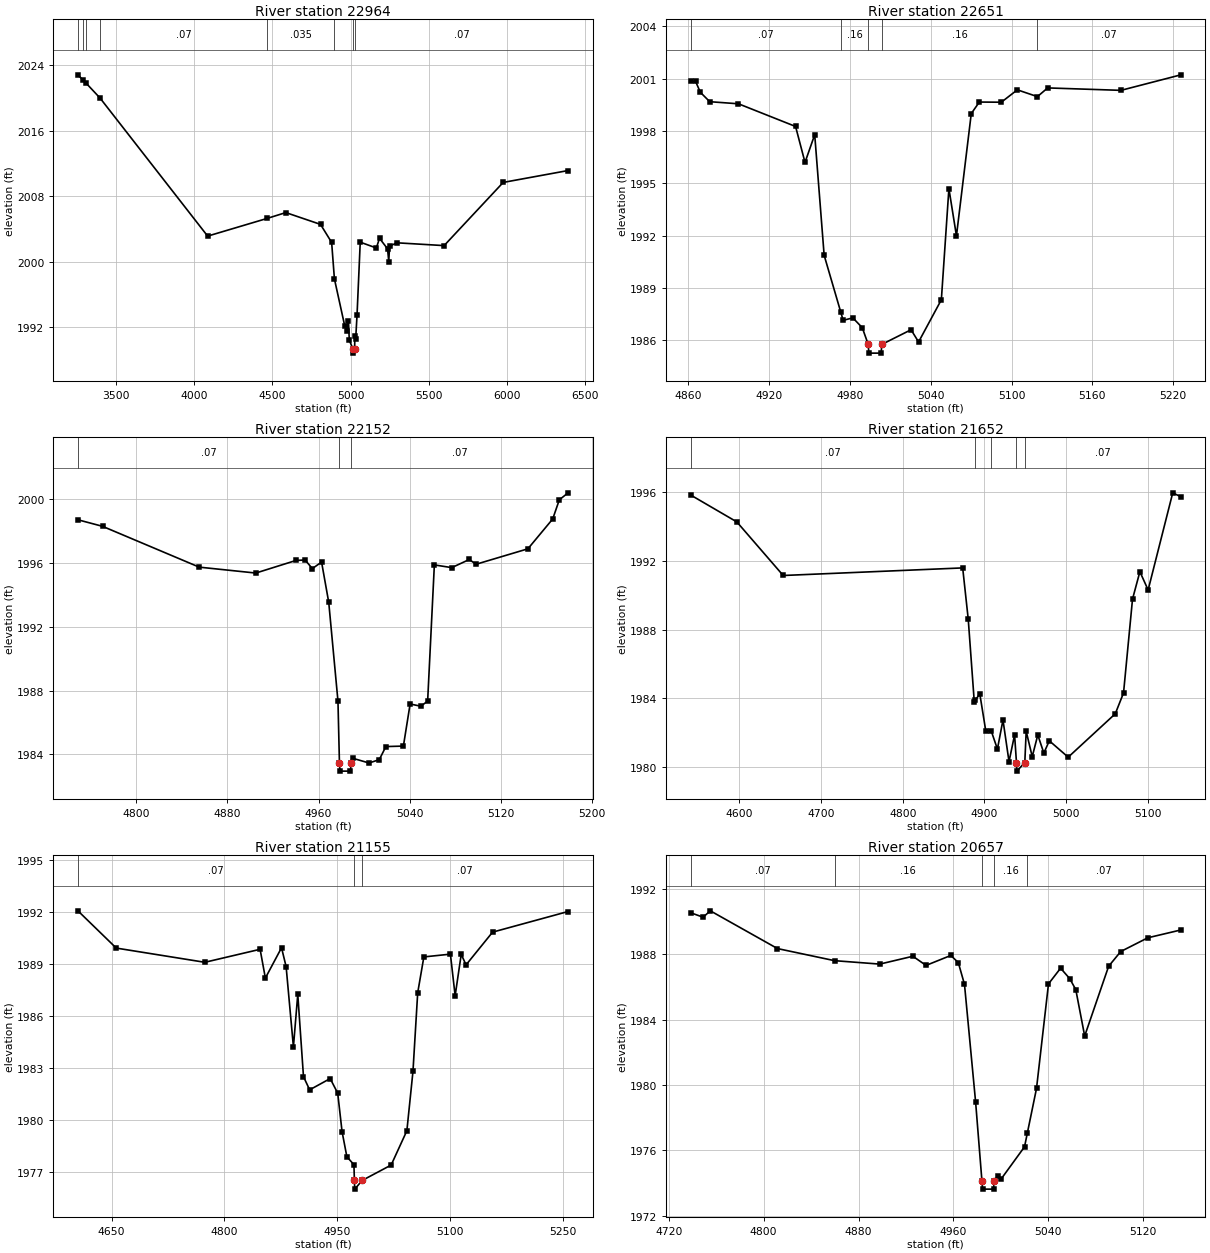
Type RM Length L Ch R = 1 ,22964   ,313,313,313
BEGIN DESCRIPTION:
Little Stink Creek 25.0
END DESCRIPTION:
XS GIS Cut Line= 3
      1427254.98      6862588.01      1428873.24      6861938.35
      1429192.74      6860584.13
#Sta/Elev= 30
  3256.2 2022.82    3290 2022.16  3305.8 2021.86  3397.9 2019.98    4086 2003.14
    4465 2005.29    4586 2006.01  4807.9 2004.57  4879.1 2002.37  4896.8 1997.92
  4962.4 1992.22  4980.3 1991.58  4986.6 1992.79    4992 1990.42  5015.9 1989.36
  5016.4 1988.86    5026 1989.36  5027.7 1990.89  5032.9  1990.6  5041.5 1993.51
    5062  2002.4    5165 2001.69  5185.3 2002.87  5236.7 2001.59  5244.5 2000.03
  5249.6 2001.93  5298.3 2002.32  5598.5 2001.98  5976.4 2009.69  6391.4 2011.14
#Mann= 8 ,-1 , 0
  3256.2     .16       0    3290     .07       0  3305.8    .035       0
  3397.9     .07       0    4465    .035       0  4896.8     .07       0
  5015.9     .07       0    5026     .07       0
Bank Sta=5015.9,5026
XS Rating Curve= 0 ,0
Exp/Cntr=0.3,0.1

Type RM Length L Ch R = 1 ,22651   ,499,499,499
BEGIN DESCRIPTION:
Little Stink Creek 24.0
END DESCRIPTION:
XS GIS Cut Line= 3
      1429054.97      6861938.03      1429153.37      6861841.13
        1429055.      6861637.99
#Sta/Elev= 30
  4861.9 2000.84  4865.5 2000.84    4869 2000.22    4876 1999.68  4897.3 1999.56
  4939.7 1998.26  4946.7  1996.2  4953.9 1997.79  4960.9 1990.88  4973.2 1987.63
    4975 1987.15  4982.2 1987.29  4989.2 1986.73  4993.6 1985.77  4994.1 1985.27
  5003.2 1985.27  5003.7 1985.77  5025.4 1986.61    5031 1985.91  5047.9 1988.33
  5053.5  1994.7  5059.1 1991.99  5070.1    1999  5076.1 1999.66  5092.4 1999.65
  5104.3 2000.36  5119.2 1999.97  5126.8 2000.47  5181.2 2000.33  5225.7 2001.22
#Mann= 5 ,-1 , 0
  4861.9     .07       0  4973.2     .16       0  4993.6     .07       0
  5003.7     .16       0  5119.2     .07       0
Bank Sta=4993.6,5003.7
XS Rating Curve= 0 ,0
Exp/Cntr=0.3,0.1

Type RM Length L Ch R = 1 ,22152   ,500,500,500
BEGIN DESCRIPTION:
Little Stink Creek 23.0
END DESCRIPTION:
XS GIS Cut Line= 3
      1429305.03      6862387.97      1429460.52      6862190.43
      1429554.98      6862038.03
#Sta/Elev= 30
  4748.6 1998.71  4770.2  1998.3  4855.2 1995.74  4904.9 1995.37  4940.2 1996.16
  4948.2 1996.19  4954.6 1995.65  4962.7 1996.06    4969 1993.53  4977.1 1987.34
  4978.4 1983.45  4978.9 1982.95  4988.1 1982.95  4988.6 1983.45  4990.4 1983.75
  5004.4 1983.46  5013.4 1983.67  5019.2 1984.49  5034.6 1984.52  5040.5 1987.16
  5049.9 1987.02  5055.9 1987.34  5061.8 1995.88  5077.1 1995.71  5092.5 1996.22
  5098.4 1995.92    5144 1996.89  5165.8 1998.76  5171.6 1999.96  5179.3  2000.4
#Mann= 3 ,-1 , 0
  4748.6     .07       0  4978.4     .07       0  4988.6     .07       0
Bank Sta=4978.4,4988.6
XS Rating Curve= 0 ,0
Exp/Cntr=0.3,0.1

Type RM Length L Ch R = 1 ,21652   ,497,497,497
BEGIN DESCRIPTION:
Little Stink Creek 22.0
END DESCRIPTION:
XS GIS Cut Line= 3
      1429505.02      6862787.98      1429843.89      6862477.95
        1429855.      6862337.99
#Sta/Elev= 30
  4540.7 1995.81  4597.1 1994.25  4653.8 1991.14  4873.4 1991.58  4880.2  1988.6
  4887.6 1983.79    4889 1983.89  4894.3 1984.28  4901.7  1982.1  4908.2 1982.13
  4915.9 1981.06  4922.7 1982.75  4930.1 1980.33  4936.9 1981.89  4939.2 1980.28
  4939.7 1979.78  4949.4 1980.28  4951.1 1982.09  4958.5 1980.62  4965.3 1981.88
  4972.7 1980.83  4979.4 1981.54  5002.5 1980.59  5060.1 1983.11  5070.2 1984.32
  5081.2 1989.77  5090.2 1991.36  5100.3  1990.3  5130.4 1995.94  5140.4 1995.71
#Mann= 5 ,-1 , 0
  4540.7     .07       0    4889     .16       0  4908.2     .07       0
  4939.2     .07       0  4949.4     .07       0
Bank Sta=4939.2,4949.4
XS Rating Curve= 0 ,0
Exp/Cntr=0.3,0.1

Type RM Length L Ch R = 1 ,21155   ,498,498,498
BEGIN DESCRIPTION:
Little Stink Creek 21.0
END DESCRIPTION:
XS GIS Cut Line= 3
      1429755.02      6862987.99      1430097.06      6862791.01
      1430254.99      6862588.01
#Sta/Elev= 30
  4605.3 1992.08  4656.3 1989.93  4774.1 1989.11  4847.6 1989.86  4854.6  1988.2
  4876.1 1989.95  4882.2 1988.86  4891.9 1984.23  4897.7 1987.26  4905.3 1982.51
  4913.5 1981.75  4940.8  1982.4  4950.8 1981.56  4956.6 1979.34    4963 1977.89
  4972.4 1977.43    4973 1976.52  4973.5 1976.02  4983.3 1976.52  5021.9 1977.41
  5042.8 1979.39  5050.9 1982.81  5057.2 1987.35  5065.4 1989.42  5100.7 1989.58
    5107 1987.18  5115.1 1989.57  5121.5 1988.96  5156.8 1990.85  5257.2 1992.04
#Mann= 3 ,-1 , 0
  4605.3     .07       0    4973     .07       0  4983.3     .07       0
Bank Sta=4973,4983.3
XS Rating Curve= 0 ,0
Exp/Cntr=0.3,0.1

Type RM Length L Ch R = 1 ,20657   ,479,479,479
BEGIN DESCRIPTION:
Little Stink Creek 20.0
END DESCRIPTION:
XS GIS Cut Line= 3
      1429804.99        6863138.       1430055.4        6863213.
      1430205.03        6863188.
#Sta/Elev= 30
  4738.6 1990.53    4749 1990.26  4755.1 1990.65  4811.7 1988.34  4859.8  1987.6
  4897.9 1987.39  4925.8 1987.87  4936.9 1987.31  4957.8 1987.92  4964.1 1987.48
  4969.3 1986.15  4978.7 1978.93    4984 1974.12  4984.5 1973.62  4993.8 1973.62
  4994.3 1974.12  4997.2 1974.44    5000 1974.22  5019.9 1976.21  5022.3 1977.06
    5030 1979.78  5040.1 1986.18  5050.3 1987.14    5058  1986.5  5063.1 1985.83
  5070.6 1982.99  5090.8 1987.26    5101 1988.16  5123.8    1989  5151.7 1989.48
#Mann= 5 ,-1 , 0
  4738.6     .07       0  4859.8     .16       0    4984     .07       0
  4994.3     .16       0  5022.3     .07       0
Bank Sta=4984,4994.3
XS Rating Curve= 0 ,0
Exp/Cntr=0.3,0.1

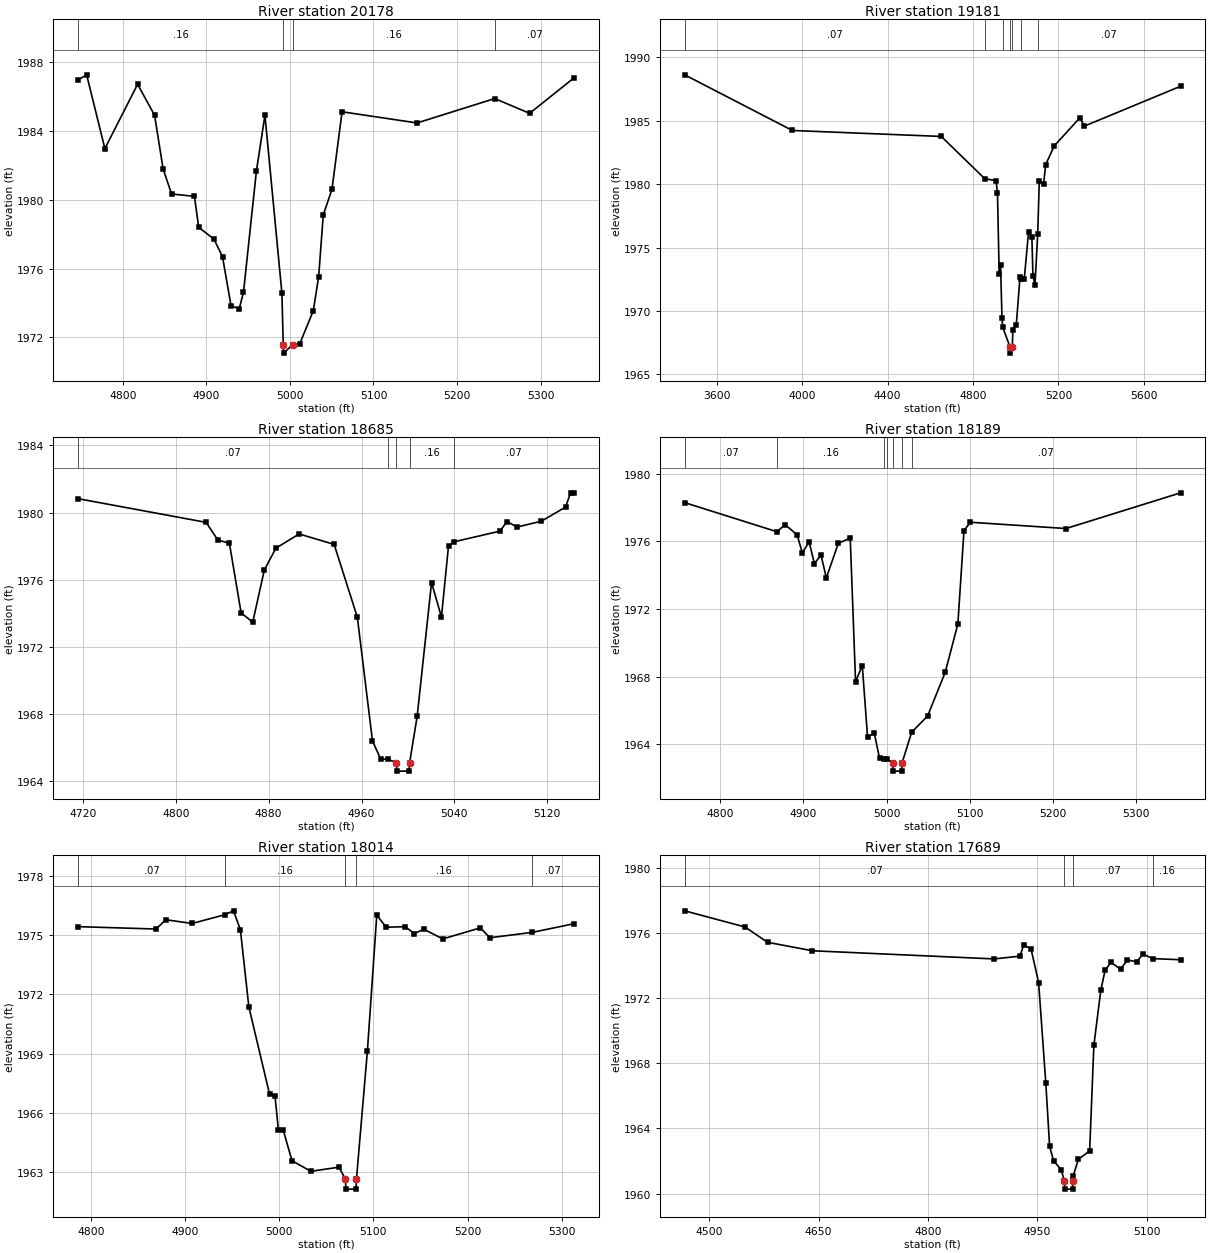
Type RM Length L Ch R = 1 ,20178   ,997,997,997
BEGIN DESCRIPTION:
Little Stink Creek 19.0
END DESCRIPTION:
XS GIS Cut Line= 3
      1429855.04      6863687.99      1430104.43       6863643.1
      1430254.99      6863338.03
#Sta/Elev= 30
  4746.6 1986.99  4756.7 1987.28  4778.5 1982.99  4817.7 1986.73    4838 1984.93
  4848.2 1981.81  4858.3 1980.35  4885.7 1980.21  4890.8 1978.41  4909.1 1977.72
  4919.3  1976.7  4929.5 1973.85  4939.3 1973.67  4944.4 1974.62  4959.9 1981.69
  4970.1 1984.93  4990.4 1974.58    4992 1971.59  4992.5 1971.09  5003.4 1971.59
  5011.9 1971.65    5028 1973.56  5034.4 1975.54  5039.9 1979.13  5050.3 1980.61
  5062.4 1985.13  5152.2 1984.48  5245.1  1985.9  5286.9 1985.04  5340.2 1987.11
#Mann= 4 ,-1 , 0
  4746.6     .16       0    4992     .07       0  5003.4     .16       0
  5245.1     .07       0
Bank Sta=4992,5003.4
XS Rating Curve= 0 ,0
Exp/Cntr=0.3,0.1

Type RM Length L Ch R = 1 ,19181   ,496,496,496
BEGIN DESCRIPTION:
Little Stink Creek 18.0
END DESCRIPTION:
XS GIS Cut Line= 3
      1429554.99      6864638.01      1430754.91      6863657.95
        1430705.      6862887.97
#Sta/Elev= 30
  3450.7 1988.63  3954.7 1984.24  4651.5 1983.77  4854.9 1980.44  4908.1 1980.28
  4914.6 1979.29  4922.5 1972.89  4928.9 1973.65  4935.6 1969.46    4939 1968.73
  4972.8 1967.18  4973.3 1966.68  4984.2 1967.18  4986.4 1968.53  5002.5 1968.91
    5020 1972.68  5026.5 1972.55    5040 1972.55  5060.1 1976.27  5075.5 1975.84
  5080.5 1972.78  5090.1 1972.07  5102.7 1976.05  5110.2 1980.23  5130.2 1980.02
  5140.2 1981.55  5180.3 1983.03  5300.6 1985.25  5320.6 1984.58  5771.6 1987.73
#Mann= 7 ,-1 , 0
  3450.7     .07       0  4854.9     .16       0    4939     .07       0
  4972.8     .07       0  4984.2     .07       0  5026.5     .16       0
  5102.7     .07       0
Bank Sta=4972.8,4984.2
XS Rating Curve= 0 ,0
Exp/Cntr=0.3,0.1

Type RM Length L Ch R = 1 ,18685   ,496,496,496
BEGIN DESCRIPTION:
Little Stink Creek 17.0
END DESCRIPTION:
XS GIS Cut Line= 3
        1431005.      6863888.01      1430988.06      6863604.51
      1430904.99      6863487.99
#Sta/Elev= 30
    4716 1980.83  4826.2 1979.42  4836.2 1978.37  4846.2 1978.18  4856.3 1974.03
  4866.3 1973.48  4876.3 1976.59  4886.3 1977.89  4906.3 1978.73  4936.4 1978.11
  4956.4 1973.77  4969.4 1966.42  4976.5 1965.32  4982.4 1965.32    4990 1965.11
  4990.5 1964.61  5000.9 1964.61  5001.4 1965.11  5007.9 1967.87  5020.3 1975.84
  5028.8 1973.78  5034.9 1978.02  5039.4 1978.26  5079.2  1978.9  5085.3 1979.47
  5093.9 1979.14  5114.8 1979.49  5135.7 1980.33    5140 1981.18  5143.1 1981.18
#Mann= 5 ,-1 , 0
    4716     .07       0  4982.4     .16       0    4990     .07       0
  5001.4     .16       0  5039.4     .07       0
Bank Sta=4990,5001.4
XS Rating Curve= 0 ,0
Exp/Cntr=0.3,0.1

Type RM Length L Ch R = 1 ,18189   ,175,175,175
BEGIN DESCRIPTION:
Little Stink Creek 16.0
END DESCRIPTION:
XS GIS Cut Line= 3
      1431204.99        6863838.      1431395.29      6863686.73
      1431204.99      6863387.99
#Sta/Elev= 30
  4756.9 1978.28  4868.1 1976.56  4877.8 1976.98  4892.3 1976.38  4898.7 1975.29
  4906.7 1975.98  4913.1 1974.68  4921.1 1975.18  4927.5 1973.83  4941.9 1975.87
  4956.3 1976.19  4962.7  1967.7  4970.8 1968.65  4977.2  1964.4  4985.2 1964.67
  4991.6 1963.17  4997.2  1963.1  5000.7  1963.1  5007.3 1962.91  5007.8 1962.41
  5018.3 1962.41  5018.8 1962.91  5030.3 1964.71  5049.5 1965.67  5070.6 1968.24
  5085.9  1971.1  5093.3 1976.63  5101.1 1977.12  5216.2 1976.75  5354.2 1978.86
#Mann= 7 ,-1 , 0
  4756.9     .07       0  4868.1     .16       0  4997.2     .07       0
  5000.7     .16       0  5007.3     .07       0  5018.8     .16       0
  5030.3     .07       0
Bank Sta=5007.3,5018.8
XS Rating Curve= 0 ,0
Exp/Cntr=0.3,0.1

Type RM Length L Ch R = 1 ,18014   ,325,325,325
BEGIN DESCRIPTION:
Little Stink Creek 4286
END DESCRIPTION:
XS GIS Cut Line= 3
      1431453.59      6863830.26       1431553.5      6863641.47
      1431538.65      6863328.52
#Sta/Elev= 30
  4786.4 1975.42    4869  1975.3  4879.5 1975.77  4907.4 1975.58  4941.9 1976.02
  4951.4 1976.22  4958.7 1975.26  4967.7 1971.36  4989.7 1966.95  4995.4 1966.88
  4999.1 1965.14  5004.2 1965.14  5013.5 1963.59  5033.5 1963.05  5063.5 1963.26
  5070.3 1962.65  5070.8 1962.15  5081.5 1962.15    5082 1962.65  5093.6 1969.11
  5103.6    1976  5113.6 1975.39  5133.6 1975.42  5143.6 1975.07  5153.6 1975.29
  5173.7  1974.8  5213.7 1975.36  5223.7 1974.86  5268.7 1975.13  5313.3 1975.57
#Mann= 5 ,-1 , 0
  4786.4     .07       0  4941.9     .16       0  5070.3     .07       0
    5082     .16       0  5268.7     .07       0
Bank Sta=5070.3,5082
XS Rating Curve= 0 ,0
Exp/Cntr=0.3,0.1

Type RM Length L Ch R = 1 ,17689   ,497,497,497
BEGIN DESCRIPTION:
Little Stink Creek 15.0
END DESCRIPTION:
XS GIS Cut Line= 3
      1431304.95      6863938.01      1431821.72      6863804.63
      1431946.06      6863726.97
#Sta/Elev= 30
  4466.3 1977.35    4549 1976.36    4580 1975.42  4641.6  1974.9  4890.7  1974.4
  4926.2 1974.57  4931.4 1975.25  4941.4 1975.02  4951.8 1972.95  4961.7 1966.77
  4966.9  1962.9  4972.4 1962.01  4982.7 1961.48  4987.2 1960.78  4987.7 1960.28
  4998.4 1960.28  4998.9 1960.78  4999.1 1961.08  5006.4 1962.11  5021.8 1962.62
  5027.6  1969.1  5037.1 1972.47    5043  1973.7    5051 1974.19  5064.2 1973.77
  5073.7 1974.34  5086.4 1974.22  5094.9  1974.7  5108.3 1974.42  5146.6 1974.35
#Mann= 4 ,-1 , 0
  4466.3     .07       0  4987.2     .07       0  4998.9     .07       0
  5108.3     .16       0
Bank Sta=4987.2,4998.9
XS Rating Curve= 0 ,0
Exp/Cntr=0.3,0.1

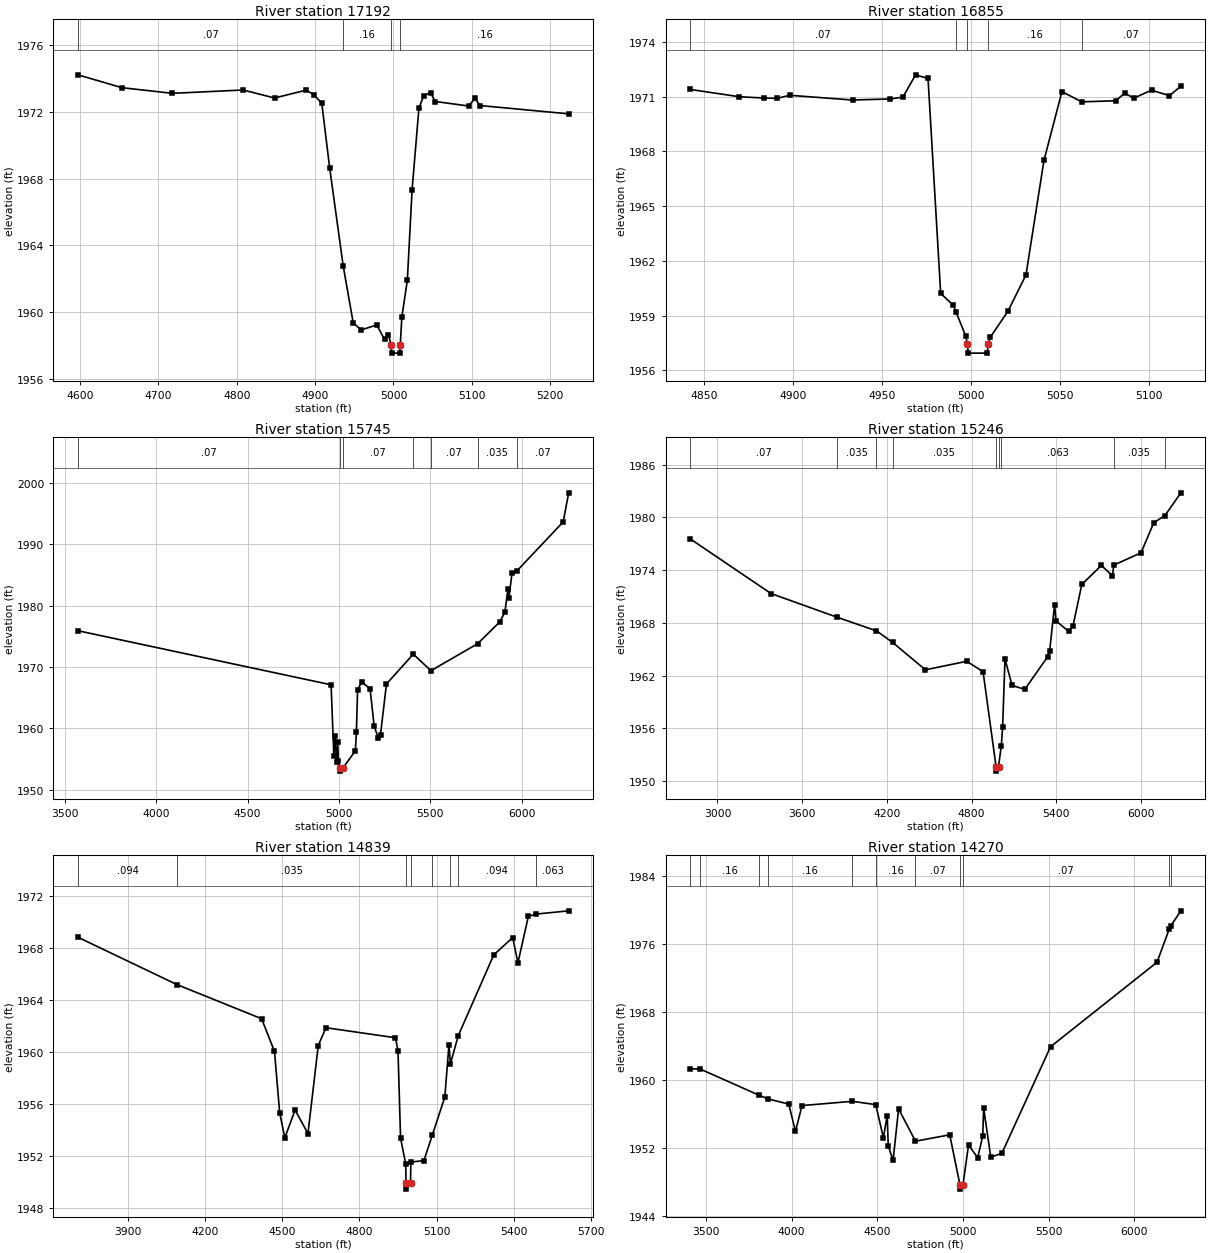
Type RM Length L Ch R = 1 ,17192   ,337,337,337
BEGIN DESCRIPTION:
Little Stink Creek 14.0
END DESCRIPTION:
XS GIS Cut Line= 3
      1431504.95        6864138.      1431906.18      6864173.58
      1432089.89      6864045.94
#Sta/Elev= 30
  4597.2 1974.22  4653.2 1973.45  4717.7 1973.11  4808.1 1973.31  4848.2 1972.83
  4888.4  1973.3  4898.4 1973.03  4908.5 1972.51  4918.5 1968.66  4935.8 1962.77
  4948.6 1959.35  4958.7 1958.92  4978.7 1959.22  4988.6 1958.35  4993.6 1958.63
    4997 1958.03  4997.5 1957.53  5008.2 1957.53  5008.7 1958.03  5010.7  1959.7
  5017.7 1961.89  5023.8 1967.33  5032.5 1972.22  5038.6 1972.98  5047.3 1973.14
  5053.5 1972.62    5096 1972.35  5104.1 1972.82  5110.2 1972.38  5223.7 1971.88
#Mann= 4 ,-1 , 0
  4597.2     .07       0  4935.8     .16       0    4997     .07       0
  5008.7     .16       0
Bank Sta=4997,5008.7
XS Rating Curve= 0 ,0
Exp/Cntr=0.3,0.1

Type RM Length L Ch R = 1 ,16855   ,1110,1110,1110
BEGIN DESCRIPTION:
Little Stink Creek 4344
END DESCRIPTION:
XS GIS Cut Line= 3
      1432038.49      6864500.49      1432149.79       6864388.5
      1432163.73      6864271.62
#Sta/Elev= 30
  4842.1 1971.39  4869.7 1970.99  4883.8 1970.92  4890.9  1970.9    4898 1971.07
  4933.3 1970.81  4954.5 1970.87  4961.6 1970.97  4968.7 1972.19  4975.7 1971.99
  4982.8 1960.22  4989.9 1959.57  4991.4 1959.21  4996.8  1957.9  4997.8 1957.45
  4998.3 1956.95    5009 1956.95  5009.5 1957.45  5010.6 1957.81  5020.6 1959.25
  5030.7 1961.23  5040.8  1967.5  5050.9 1971.27    5062 1970.71  5081.1 1970.77
  5086.2 1971.19  5091.2 1970.91  5101.2 1971.35  5111.3 1971.05  5117.7 1971.57
#Mann= 5 ,-1 , 0
  4842.1     .07       0  4991.4     .16       0  4997.8     .07       0
  5009.5     .16       0    5062     .07       0
Bank Sta=4997.8,5009.5
XS Rating Curve= 0 ,0
Exp/Cntr=0.3,0.1

Type RM Length L Ch R = 1 ,15745   ,499,499,499
BEGIN DESCRIPTION:
Little Stink Creek 13.0
END DESCRIPTION:
XS GIS Cut Line= 3
        1431305.        6864288.      1432494.89      6865077.35
      1433605.04      6864487.98
#Sta/Elev= 30
  3572.1 1975.89    4957 1967.09  4972.1 1955.56  4978.1 1958.83  4987.1 1954.45
  4993.1 1957.82  4997.1 1954.69  5004.8 1953.53  5005.3 1953.03  5021.6 1953.53
  5089.8 1956.34  5095.5 1959.36    5102  1966.3  5124.7 1967.55    5170 1966.46
  5192.6 1960.39  5215.2  1958.4  5227.4 1958.96    5260 1967.22  5406.6 1972.08
  5503.4 1969.39  5758.9 1973.78  5880.6 1977.35  5908.3 1978.97  5924.6 1982.74
  5930.2 1981.28  5946.6 1985.23  5972.2 1985.59  6226.7 1993.61  6256.9 1998.35
#Mann= 7 ,-1 , 0
  3572.1     .07       0  5004.8     .07       0  5021.6     .07       0
  5406.6    .035       0  5503.4     .07       0  5758.9    .035       0
  5972.2     .07       0
Bank Sta=5004.8,5021.6
XS Rating Curve= 0 ,0
Exp/Cntr=0.3,0.1

Type RM Length L Ch R = 1 ,15246   ,407,407,407
BEGIN DESCRIPTION:
Little Stink Creek 12.0
END DESCRIPTION:
XS GIS Cut Line= 3
      1430655.04        6865188.      1432837.92      6865404.65
      1434116.19      6865290.04
#Sta/Elev= 30
  2806.4 1977.57  3379.2 1971.34  3845.7 1968.65  4126.4 1967.09  4241.1 1965.77
  4473.3 1962.65  4765.9 1963.62  4881.8 1962.44    4974 1951.61  4974.5 1951.11
  4991.3 1951.61  5010.8 1953.98  5020.3 1956.09  5037.2 1963.88  5087.4 1960.87
  5177.8 1960.43  5338.4 1964.12    5354 1964.85  5388.6 1970.05  5398.7 1968.22
    5489 1967.02  5519.2 1967.67  5581.4 1972.37    5720 1974.54  5798.8 1973.37
    5808 1974.58  6001.1 1975.98  6091.4 1979.41  6170.6 1980.22  6283.4 1982.81
#Mann= 9 ,-1 , 0
  2806.4     .07       0  3845.7    .035       0  4126.4     .07       0
  4241.1    .035       0    4974    .035       0  4991.3    .035       0
  5010.8    .063       0    5808    .035       0  6170.6     .07       0
Bank Sta=4974,4991.3
XS Rating Curve= 0 ,0
Exp/Cntr=0.3,0.1

Type RM Length L Ch R = 1 ,14839   ,569,569,569
BEGIN DESCRIPTION:
Little Stink Creek 11.0
END DESCRIPTION:
XS GIS Cut Line= 3
      1431561.06       6865810.2      1432854.98       6865788.5
      1433459.43      6865683.55
#Sta/Elev= 30
  3705.9 1968.81  4091.1 1965.17  4419.9 1962.55  4469.9 1960.04    4490 1955.34
    4510  1953.4    4550 1955.54    4600 1953.73    4640 1960.49    4670 1961.86
    4940 1961.09    4950  1960.1    4960 1953.38    4980 1951.39  4981.3 1949.96
  4981.8 1949.46  4998.7 1949.96    5000 1951.54  5050.8 1951.65  5083.3 1953.61
    5132 1956.53  5148.1 1960.54  5153.8 1959.09  5184.3 1961.25  5322.1 1967.45
  5395.9 1968.79  5416.2 1966.84  5456.8 1970.42  5487.3 1970.59  5613.5 1970.84
#Mann= 8 ,-1 , 0
  3705.9    .094       0  4091.1    .035       0  4981.3    .035       0
  4998.7    .035       0  5083.3     .16       0  5153.8    .063       0
  5184.3    .094       0  5487.3    .063       0
Bank Sta=4981.3,4998.7
XS Rating Curve= 0 ,0
Exp/Cntr=0.3,0.1

Type RM Length L Ch R = 1 ,14270   ,286,286,286
BEGIN DESCRIPTION:
Little Stink Creek 10.0
END DESCRIPTION:
XS GIS Cut Line= 3
      1431664.05        6866934.      1433104.87      6866258.05
      1434278.92       6865769.6
#Sta/Elev= 30
  3408.5 1961.34  3466.6 1961.32  3812.5 1958.22  3859.9 1957.82  3983.9 1957.19
  4022.8 1953.98  4061.2 1957.02  4354.8 1957.52  4491.5 1957.13  4535.8 1953.23
  4558.3 1955.85  4564.2 1952.29  4592.5 1950.56  4624.6 1956.63  4723.2 1952.83
    4923 1953.58  4982.7 1947.69  4983.2 1947.19  5000.2 1947.69  5032.6 1952.38
  5086.3 1950.89  5115.6 1953.45    5121  1956.7  5162.6 1950.94  5227.6 1951.42
  5511.2 1963.94  6132.3 1973.88  6204.1 1977.81  6211.7 1978.13  6271.6 1979.93
#Mann= 11 ,-1 , 0
  3408.5     .07       0  3466.6     .16       0  3812.5     .07       0
  3859.9     .16       0  4354.8     .07       0  4491.5     .16       0
  4723.2     .07       0  4982.7     .07       0  5000.2     .07       0
  6204.1    .035       0  6211.7    .094       0
Bank Sta=4982.7,5000.2
XS Rating Curve= 0 ,0
Exp/Cntr=0.3,0.1

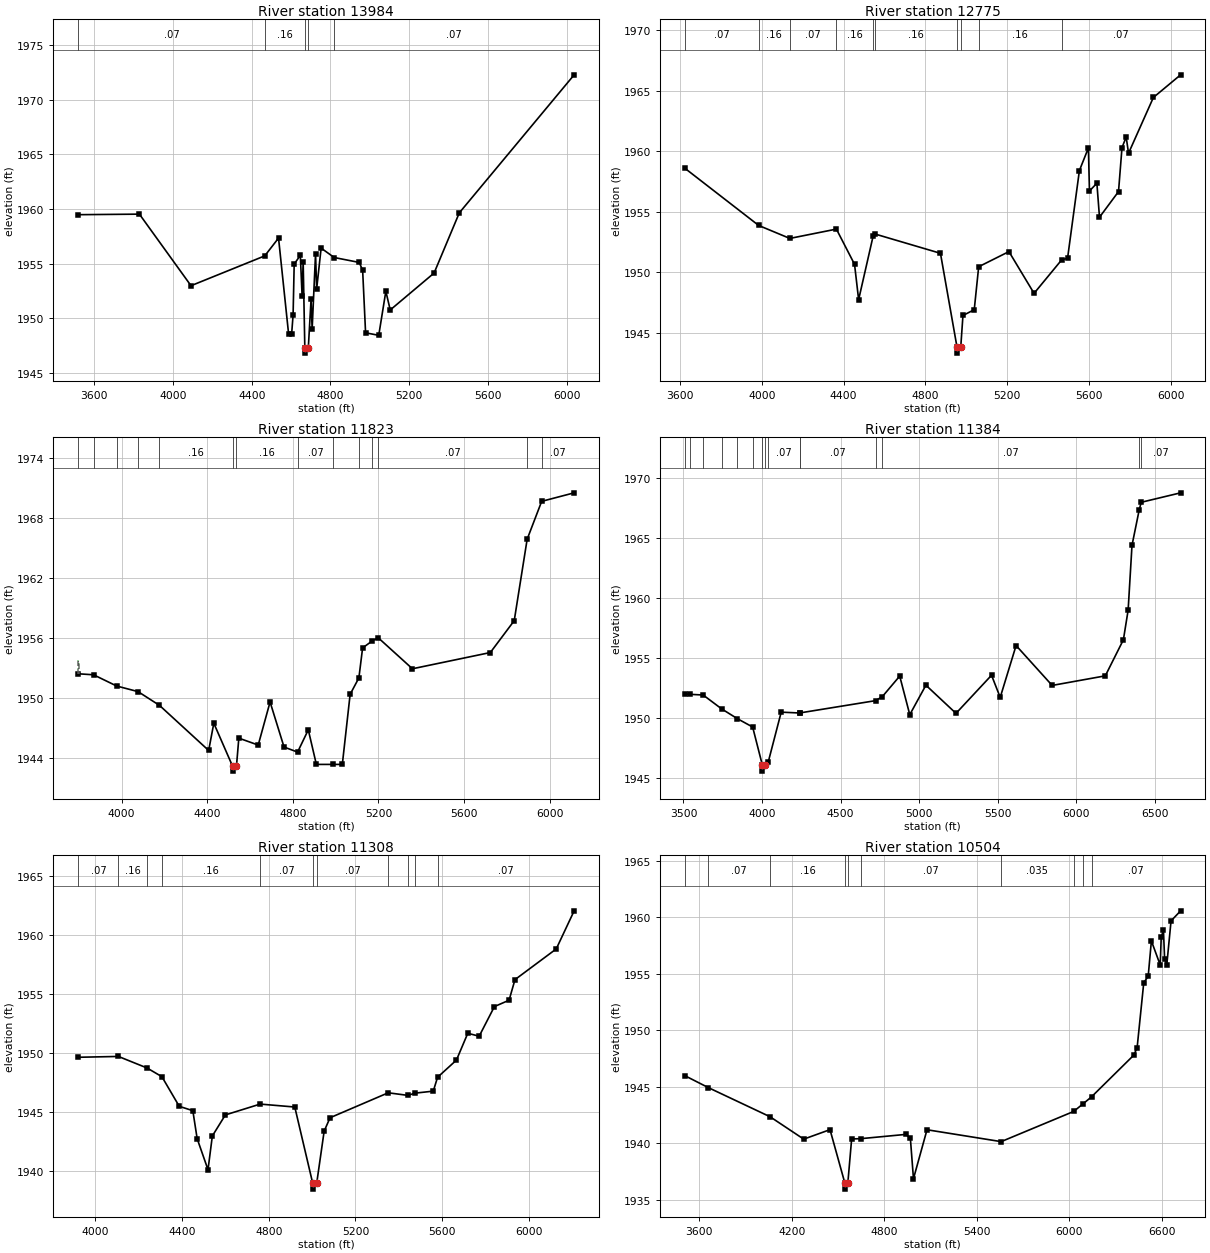
Type RM Length L Ch R = 1 ,13984   ,1209,1209,1209
BEGIN DESCRIPTION:
Little Stink Creek 9.1
END DESCRIPTION:
XS GIS Cut Line= 3
      1431843.66      6867147.48      1433184.72      6866518.12
      1434110.57      6866049.69
#Sta/Elev= 30
  3518.6 1959.48  3829.4 1959.53  4091.5 1952.98  4466.1 1955.71  4536.1 1957.34
  4587.2 1948.57  4602.6 1948.56    4610 1950.29  4615.6 1954.96  4646.8 1955.76
  4655.7 1952.08  4661.2 1955.18  4669.6 1947.31  4670.1 1946.81  4687.4 1947.31
  4701.3 1951.73  4706.8 1949.01  4724.1 1955.92  4729.6 1952.66  4752.4 1956.42
    4819 1955.56    4946 1955.11  4963.3 1954.39  4978.2 1948.67  5045.1 1948.44
  5081.1 1952.47  5103.4 1950.76  5326.2 1954.14  5454.3 1959.65  6037.6 1972.28
#Mann= 5 ,-1 , 0
  3518.6     .07       0  4466.1     .16       0  4669.6     .07       0
  4687.4     .16       0    4819     .07       0
Bank Sta=4669.6,4687.4
XS Rating Curve= 0 ,0
Exp/Cntr=0.3,0.1

Type RM Length L Ch R = 1 ,12775   ,952,952,952
BEGIN DESCRIPTION:
Little Stink Creek 9.0
END DESCRIPTION:
XS GIS Cut Line= 3
      1432054.63      6867172.67      1433431.18      6867161.14
      1434455.05      6866937.99
#Sta/Elev= 30
  3623.4 1958.62  3985.3 1953.88  4137.4 1952.81  4365.1 1953.58  4453.8 1950.67
  4473.8 1947.75    4545 1953.03  4554.7 1953.17  4873.8 1951.58  4954.7 1943.83
  4955.2 1943.33    4973 1943.83  4983.8 1946.44    5039 1946.92  5060.7 1950.47
  5208.6 1951.72  5331.4 1948.27  5466.5 1951.04  5495.2 1951.17  5553.1 1958.42
  5597.1 1960.29  5602.2 1956.73  5638.5 1957.37  5651.3 1954.56  5744.3 1956.68
  5761.3 1960.31  5781.7 1961.19  5793.3 1959.85  5914.8 1964.46  6047.9 1966.33
#Mann= 10 ,-1 , 0
  3623.4     .07       0  3985.3     .16       0  4137.4     .07       0
  4365.1     .16       0    4545     .07       0  4554.7     .16       0
  4954.7     .07       0    4973     .16       0  5060.7     .16       0
  5466.5     .07       0
Bank Sta=4954.7,4973
XS Rating Curve= 0 ,0
Exp/Cntr=0.3,0.1

Type RM Length L Ch R = 1 ,11823   ,439,439,439
BEGIN DESCRIPTION:
Little Stink Creek 8.1
END DESCRIPTION:
XS GIS Cut Line= 3
      1432699.38      6867864.86      1433894.49      6867728.19
      1434889.94      6867227.01
#Sta/Elev= 30
  3797.1 1952.45  3868.8 1952.35  3976.8 1951.23  4076.8 1950.67  4176.8  1949.3
  4406.7  1944.8  4430.7 1947.52  4518.2 1943.24  4518.7 1942.74  4536.6 1943.24
  4547.6 1946.03  4638.2 1945.34  4693.6 1949.64  4758.9 1945.14  4822.2 1944.64
  4872.2 1946.86  4909.9 1943.41  4989.9 1943.41  5031.2 1943.41  5067.7  1950.4
  5108.6 1952.04    5126 1955.03  5171.2 1955.73  5198.6 1956.05  5358.8 1952.95
  5722.9 1954.57  5834.5 1957.75  5894.9 1965.87  5962.7 1969.65  6114.5  1970.5
#Mann= 14 ,-1 , 0
  3797.1    .035       0  3868.8     .07       0  3976.8    .035       0
  4076.8     .07       0  4176.8     .16       0  4518.2     .07       0
  4536.6     .16       0  4822.2     .07       0  4989.9     .12       0
  5108.6     .07       0  5171.2    .035       0  5198.6     .07       0
  5894.9    .035       0  5962.7     .07       0
#XS Ineff= 2 , 0
         3802.99 1953.74
Permanent Ineff=
       F       F
Bank Sta=4518.2,4536.6
XS Rating Curve= 0 ,0
Exp/Cntr=0.3,0.1

Type RM Length L Ch R = 1 ,11384   ,76,76,76
BEGIN DESCRIPTION:
Little Stink Creek 4288
END DESCRIPTION:
XS GIS Cut Line= 6
      1432641.59      6867911.28      1433275.62      6867901.85
        1433935.      6868156.36       1434296.8      6867877.89
      1434096.74      6867651.23      1434970.62      6867293.42
#Sta/Elev= 30
  3507.7 1952.02  3539.8 1951.98  3625.3 1951.92  3742.2 1950.77  3841.1 1949.96
  3940.1 1949.25  4001.9 1946.07  4002.4 1945.57  4020.3 1946.07  4039.1 1946.32
  4121.7 1950.49  4240.5 1950.42  4242.1 1950.43  4721.7 1951.45  4764.7 1951.78
  4875.7  1953.5  4939.7 1950.28  5042.3 1952.74  5233.7 1950.39  5459.8 1953.57
    5515 1951.72    5616 1956.05  5845.5 1952.72  6183.6 1953.52  6298.6 1956.53
  6328.7 1958.99  6353.4 1964.41    6399 1967.35  6411.8    1968  6662.7 1968.79
#Mann= 15 ,-1 , 0
  3507.7     .07       0  3539.8    .035       0  3625.3     .07       0
  3742.2    .035       0  3841.1     .07       0  3940.1     .16       0
  4001.9     .07       0  4020.3     .16       0  4039.1     .07       0
  4240.5     .16       0  4242.1     .07       0  4721.7     .16       0
  4764.7     .07       0    6399    .035       0  6411.8     .07       0
Bank Sta=4001.9,4020.3
XS Rating Curve= 0 ,0
Exp/Cntr=0.3,0.1

Type RM Length L Ch R = 1 ,11308   ,804,804,804
BEGIN DESCRIPTION:
Little Stink Creek 8.0
END DESCRIPTION:
XS GIS Cut Line= 3
      1432976.79      6868228.23      1434054.62      6868193.16
      1435090.06        6867570.
#Sta/Elev= 30
  3921.6 1949.63    4107  1949.7  4238.9 1948.72  4307.4 1947.98  4387.5 1945.46
  4450.1 1945.09  4470.1 1942.71  4520.1 1940.07  4540.1 1942.94  4600.2 1944.73
  4760.7 1945.65  4920.3  1945.4  5002.9 1938.92  5003.4 1938.42  5021.3 1938.92
  5055.7 1943.35  5082.9 1944.49  5351.2 1946.61  5441.6 1946.39  5474.6 1946.58
  5558.8 1946.75  5578.7 1947.93  5665.7 1949.39    5718 1951.67  5770.5 1951.42
  5840.8 1953.94  5908.4 1954.48  5935.6 1956.23  6125.9 1958.84  6208.5 1962.08
#Mann= 11 ,-1 , 0
  3921.6     .07       0    4107     .16       0  4238.9     .07       0
  4307.4     .16       0  4760.7     .07       0  5002.9     .07       0
  5021.3     .07       0  5351.2    .035       0  5441.6     .07       0
  5474.6    .035       0  5578.7     .07       0
Bank Sta=5002.9,5021.3
XS Rating Curve= 0 ,0
Exp/Cntr=0.3,0.1

Type RM Length L Ch R = 1 ,10504   ,1583,1583,1583
BEGIN DESCRIPTION:
Little Stink Creek 7.1
END DESCRIPTION:
XS GIS Cut Line= 3
      1432834.76      6869025.64      1434324.93      6868908.03
      1435654.07      6867810.36
#Sta/Elev= 30
  3505.2 1945.99  3659.7 1944.92  4059.4 1942.35  4277.8 1940.37  4448.4 1941.21
  4545.4 1936.45  4545.9 1935.95  4563.8 1936.45  4588.8 1940.39  4646.3 1940.41
  4940.9 1940.79    4970 1940.43    4990 1936.87  5077.9  1941.2  5559.2 1940.15
  6029.8 1942.82  6092.1 1943.51  6145.5 1944.11  6420.8 1947.81  6441.6 1948.47
  6484.6 1954.21  6513.3 1954.77  6534.1  1957.9  6591.4 1955.77  6597.9 1958.21
  6612.2 1958.88  6620.1 1956.27  6634.2 1955.81  6661.7 1959.67  6723.8 1960.56
#Mann= 10 ,-1 , 0
  3505.2    .035       0  3659.7     .07       0  4059.4     .16       0
  4545.4     .07       0  4563.8     .16       0  4646.3     .07       0
  5559.2    .035       0  6029.8     .07       0  6092.1    .035       0
  6145.5     .07       0
Bank Sta=4545.4,4563.8
XS Rating Curve= 0 ,0
Exp/Cntr=0.3,0.1

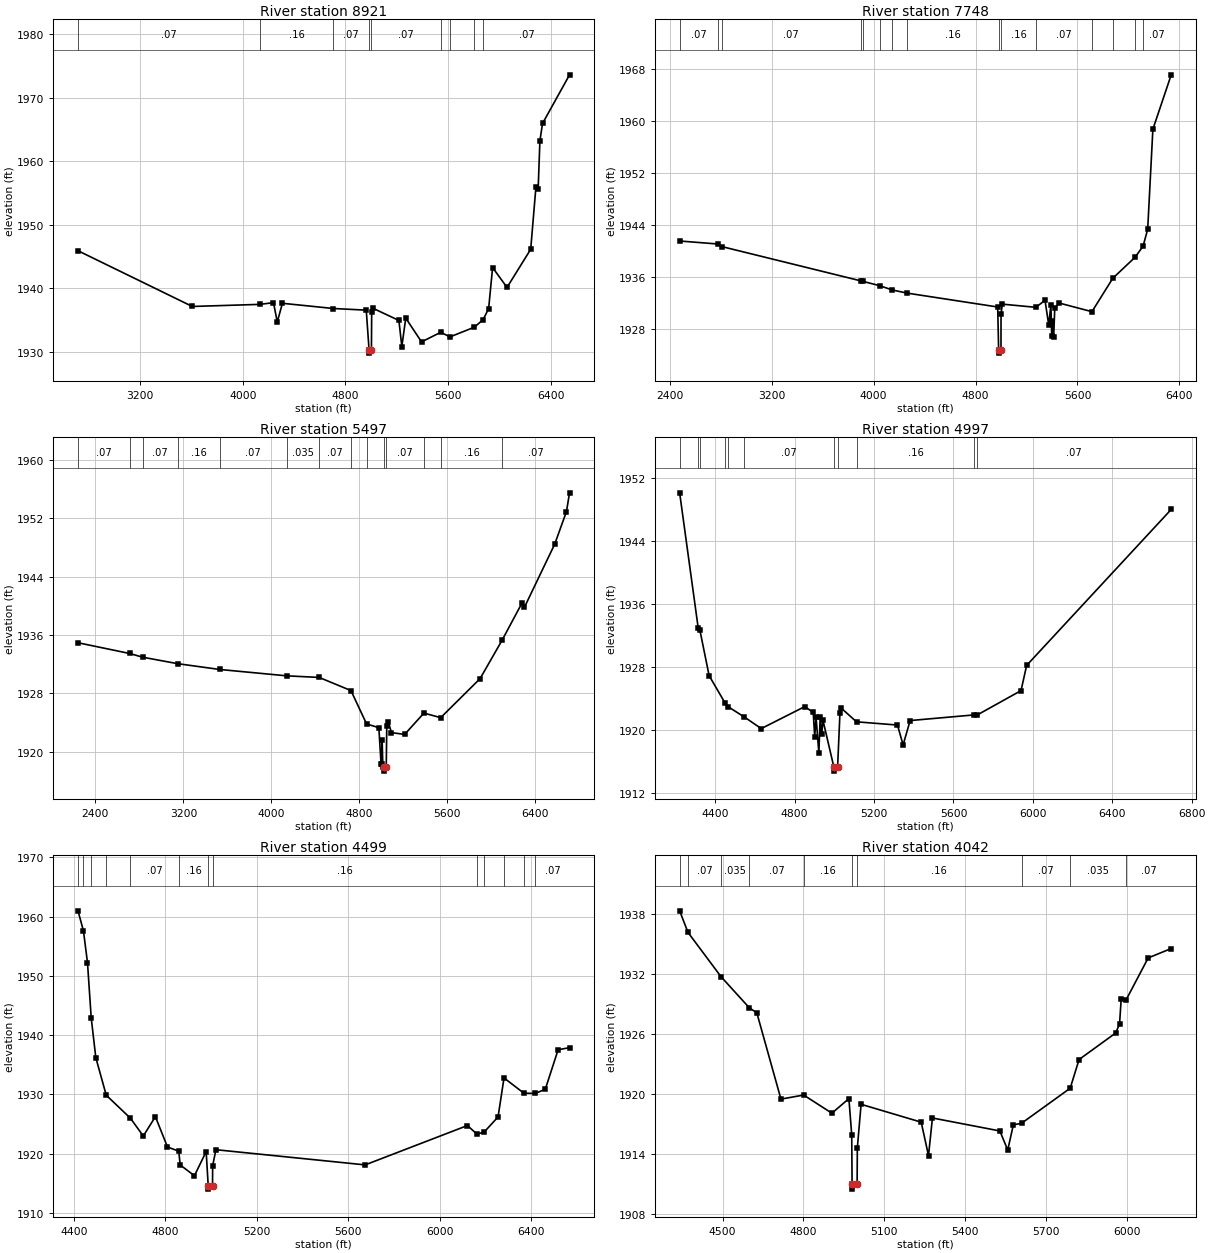
Type RM Length L Ch R = 1 ,8921    ,1173,1173,1173
BEGIN DESCRIPTION:
Little Stink Creek 7.0
END DESCRIPTION:
XS GIS Cut Line= 3
      1432714.16       6869278.7      1434921.75      6869871.48
      1436430.41      6869529.17
#Sta/Elev= 30
  2714.2 1945.89  3605.5 1937.11  4131.7 1937.44  4238.5 1937.71  4268.1 1934.67
  4308.1 1937.61  4705.8 1936.79  4961.9 1936.53  4983.8 1930.26  4984.3 1929.76
  5002.2 1930.26  5004.2 1936.22  5013.6 1936.83  5216.3 1934.91  5239.2  1930.8
  5269.9 1935.27    5393 1931.53  5542.2 1933.04  5614.9 1932.32  5805.3 1933.85
  5873.2 1935.04    5916 1936.77    5947 1943.24  6059.5 1940.11  6244.1 1946.12
  6285.1    1956  6302.1 1955.55  6315.9 1963.23  6336.4 1965.94    6547  1973.6
#Mann= 9 ,-1 , 0
  2714.2     .07       0  4131.7     .16       0  4705.8     .07       0
  4983.8     .07       0  5002.2     .07       0  5542.2    .035       0
  5614.9     .07       0  5805.3    .035       0  5873.2     .07       0
Bank Sta=4983.8,5002.2
XS Rating Curve= 0 ,0
Exp/Cntr=0.3,0.1

Type RM Length L Ch R = 1 ,7748    ,2251,2251,2251
BEGIN DESCRIPTION:
Little Stink Creek 6.0
END DESCRIPTION:
XS GIS Cut Line= 3
      1432655.01        6870088.      1435124.42      6870608.65
      1436355.01      6870087.99
#Sta/Elev= 30
  2476.3 1941.57  2775.1 1941.11  2805.5 1940.72    3900 1935.43  3914.5 1935.36
  4045.8  1934.7  4146.3 1934.03  4262.1 1933.55  4973.8 1931.41  4981.1 1924.81
  4981.6 1924.31  4999.6 1924.81    5000 1930.38  5010.3 1931.85  5273.4 1931.36
  5345.4 1932.44  5374.5 1928.64  5391.5 1931.72  5398.2  1926.9  5403.6 1929.28
  5413.2 1926.73  5421.9 1931.25  5456.7 1932.02  5713.9 1930.69  5877.5 1935.83
  6052.1 1939.06  6115.2 1940.77  6151.6 1943.37  6192.3 1958.77  6336.2 1967.15
#Mann= 15 ,-1 , 0
  2476.3     .07       0  2775.1     .16       0  2805.5     .07       0
    3900     .16       0  3914.5     .07       0  4045.8     .16       0
  4146.3     .07       0  4262.1     .16       0  4981.1     .07       0
  4999.6     .16       0  5273.4     .07       0  5713.9    .035       0
  5877.5     .07       0  6052.1    .035       0  6115.2     .07       0
Bank Sta=4981.1,4999.6
XS Rating Curve= 0 ,0
Exp/Cntr=0.3,0.1

Type RM Length L Ch R = 1 ,5497    ,500,500,500
BEGIN DESCRIPTION:
Little Stink Creek 5.0
END DESCRIPTION:
XS GIS Cut Line= 3
      1432505.04      6871088.01      1435194.87      6871697.42
      1436405.01      6870487.99
#Sta/Elev= 30
    2242 1934.94  2711.3 1933.47  2830.1 1932.96  3149.5 1932.07  3530.6 1931.28
  4138.9 1930.41  4434.7 1930.19  4723.6 1928.39  4865.6 1923.82  4977.2 1923.31
  4997.5 1918.29  5003.1 1918.29  5006.8 1921.67  5013.8 1917.89  5025.7 1917.86
  5026.2 1917.36  5044.4 1917.86  5049.2 1923.58  5063.3  1924.1  5091.6 1922.63
  5211.8 1922.39    5387 1925.31  5539.3 1924.68  5897.7 1930.03  6098.4 1935.31
  6279.5 1940.41  6300.8  1939.8  6576.5 1948.46  6682.6  1952.9  6710.9 1955.47
#Mann= 14 ,-1 , 0
    2242     .07       0  2711.3    .035       0  2830.1     .07       0
  3149.5     .16       0  3530.6     .07       0  4138.9    .035       0
  4434.7     .07       0  4723.6    .035       0  4865.6     .07       0
  5025.7     .07       0  5044.4     .07       0    5387     .07       0
  5539.3     .16       0  6098.4     .07       0
Bank Sta=5025.7,5044.4
XS Rating Curve= 0 ,0
Exp/Cntr=0.3,0.1

Type RM Length L Ch R = 1 ,4997    ,498,498,498
BEGIN DESCRIPTION:
Little Stink Creek 4.0
END DESCRIPTION:
XS GIS Cut Line= 3
      1434754.97      6872538.03      1435338.89      6872021.49
      1436554.98      6870838.02
#Sta/Elev= 30
  4220.4 1950.17  4313.6 1933.07  4322.4 1932.74  4368.9 1926.96  4449.2 1923.49
  4465.7    1923  4546.3 1921.71  4631.6 1920.24  4850.7 1923.03  4893.4 1922.29
  4900.9 1919.19  4907.6 1921.73  4921.8 1917.14  4928.5 1921.72    4936 1919.49
  4942.7 1921.28  4997.5 1915.34    4998 1914.84  5016.2 1915.34    5028  1922.2
  5035.2 1922.82  5111.5  1921.1  5317.9 1920.69  5346.2 1918.16  5381.6 1921.26
  5705.3 1921.98  5719.7 1921.97  5940.3 1925.06  5968.6 1928.26  6696.9 1948.06
#Mann= 11 ,-1 , 0
  4220.4    .035       0  4313.6     .07       0  4322.4    .035       0
  4449.2     .07       0  4465.7    .035       0  4546.3     .07       0
  4997.5     .07       0  5016.2     .07       0  5111.5     .16       0
  5705.3    .035       0  5719.7     .07       0
Bank Sta=4997.5,5016.2
XS Rating Curve= 0 ,0
Exp/Cntr=0.3,0.1

Type RM Length L Ch R = 1 ,4499    ,457,457,457
BEGIN DESCRIPTION:
Little Stink Creek 3.0
END DESCRIPTION:
XS GIS Cut Line= 3
      1434804.99        6872588.      1435354.84      6872398.17
        1436555.        6871388.
#Sta/Elev= 30
  4418.3 1960.97  4442.1  1957.6  4459.8 1952.24  4476.2 1942.87  4496.3 1936.19
  4541.8 1929.86  4647.6 1925.98    4704 1922.97  4756.9 1926.24  4809.7 1921.12
  4859.2 1920.41  4865.3 1918.09  4927.7 1916.27    4979 1920.35  4988.1 1914.51
  4988.6 1914.01  5006.8 1914.51  5007.4 1917.97  5021.7 1920.66  5674.6  1918.1
  6121.9 1924.74  6163.4  1923.3  6194.7 1923.62  6255.9 1926.19    6282 1932.77
    6369  1930.2  6419.3 1930.16  6462.7 1930.88  6518.7 1937.53  6568.7 1937.88
#Mann= 13 ,-1 , 0
  4418.3     .07       0  4442.1    .035       0  4476.2     .07       0
  4541.8    .035       0  4647.6     .07       0  4859.2     .16       0
  4988.1     .07       0  5006.8     .16       0  6163.4     .07       0
  6194.7    .035       0    6282     .07       0    6369    .035       0
  6419.3     .07       0
Bank Sta=4988.1,5006.8
XS Rating Curve= 0 ,0
Exp/Cntr=0.3,0.1

Type RM Length L Ch R = 1 ,4042    ,498,498,498
BEGIN DESCRIPTION:
Little Stink Creek 2.0
END DESCRIPTION:
XS GIS Cut Line= 3
      1435067.33      6872780.97      1435694.81       6872578.3
      1436628.38      6871881.91
#Sta/Elev= 30
  4340.6 1938.34  4371.5 1936.18  4494.2 1931.74  4599.2 1928.62    4627 1928.12
  4716.5 1919.47  4800.8 1919.88  4905.6 1918.06  4968.7 1919.52  4979.2 1915.87
  4980.5 1910.95    4981 1910.45  4999.2 1910.95    5000 1914.58  5013.9 1918.95
    5237 1917.16  5264.1 1913.81  5278.7 1917.58  5528.9 1916.28  5558.1 1914.37
  5578.9 1916.89  5609.4 1917.05  5789.8 1920.56  5822.9 1923.44  5958.4 1926.09
    5973 1926.99  5979.2 1929.53    5998 1929.45  6079.3 1933.62  6164.7 1934.56
#Mann= 10 ,-1 , 0
  4340.6    .035       0  4371.5     .07       0  4494.2    .035       0
  4599.2     .07       0  4800.8     .16       0  4980.5     .07       0
  4999.2     .16       0  5609.4     .07       0  5789.8    .035       0
    5998     .07       0
Bank Sta=4980.5,4999.2
XS Rating Curve= 0 ,0
Exp/Cntr=0.3,0.1