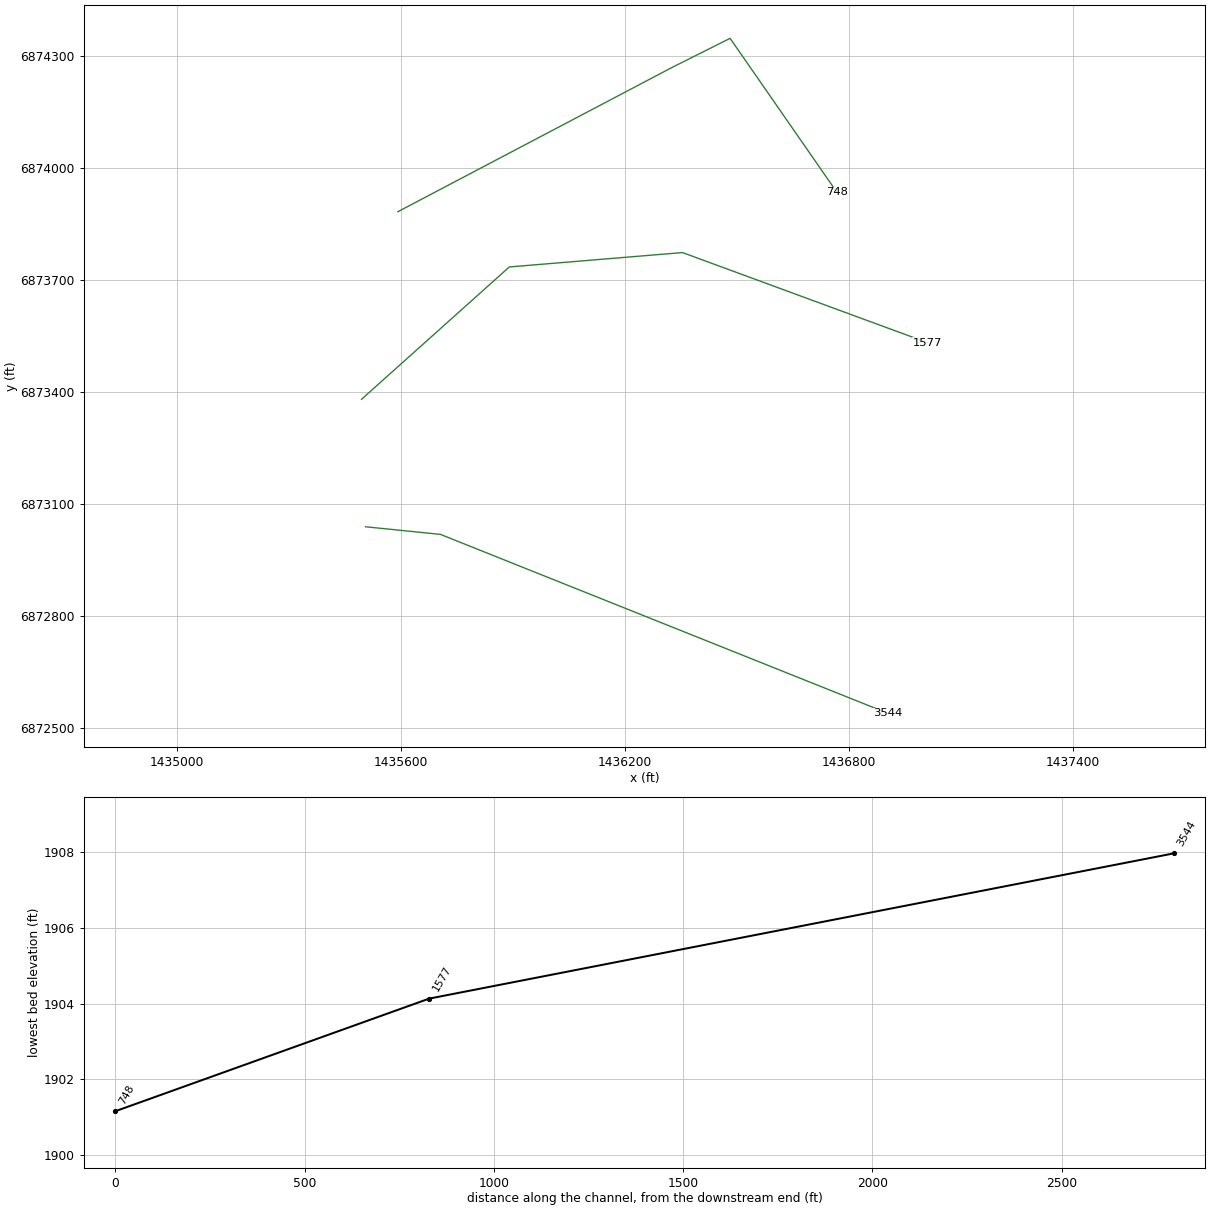
HEC-RAS study Little Stink Creek.prj: Little Stink Creek Base Level Engineering

--- Little Stink Creek.g01 (geometry) --- (continued)

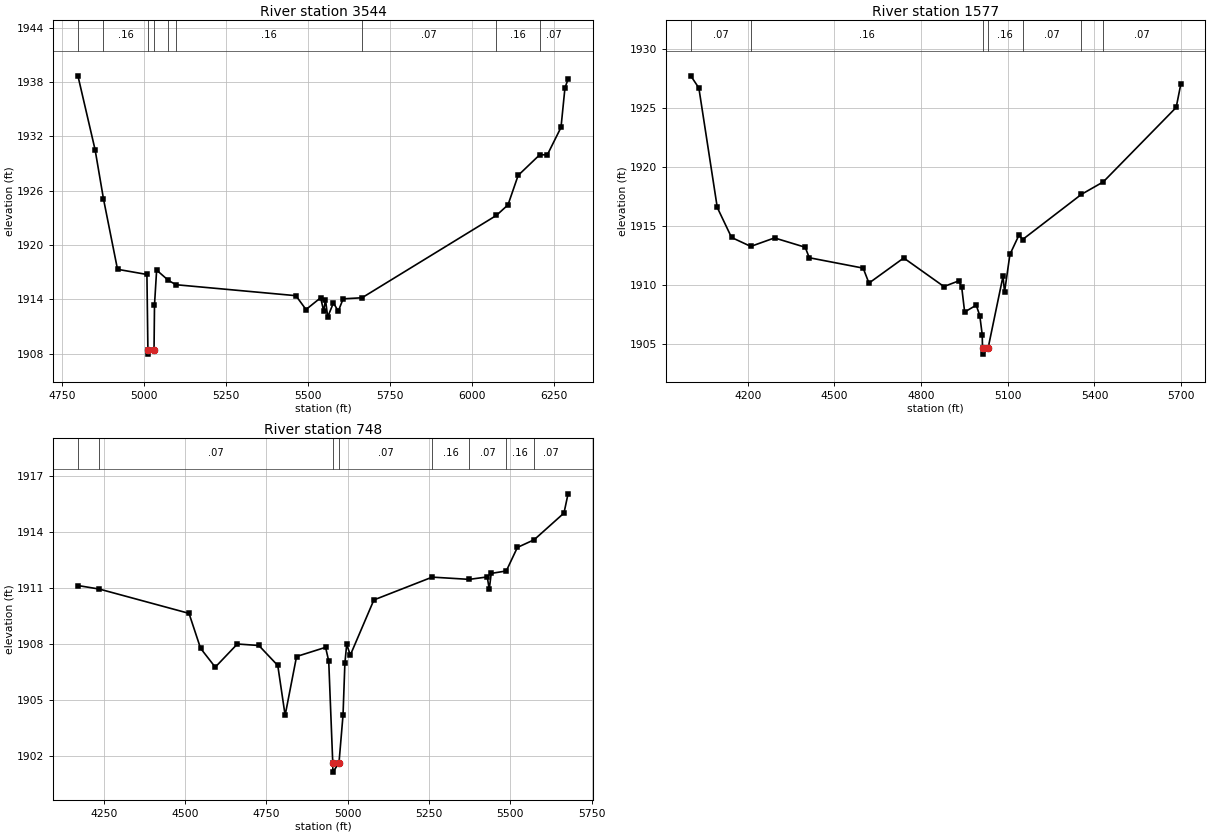
Type RM Length L Ch R = 1 ,3544    ,1967,1967,1967
BEGIN DESCRIPTION:
Little Stink Creek 1.0
END DESCRIPTION:
XS GIS Cut Line= 3
      1435505.03        6873038.      1435705.49      6873017.65
      1436904.95      6872538.02
#Sta/Elev= 30
  4798.5 1938.67  4850.9  1930.5  4876.4 1925.08  4919.1 1917.32  5008.7 1916.75
  5011.7 1908.46  5012.2 1907.96  5030.4 1908.46  5031.8 1913.39  5038.3 1917.23
  5074.1  1916.1    5097 1915.62  5462.6 1914.41  5493.4 1912.88    5538 1914.18
  5547.3 1912.71  5552.7 1913.98  5559.5 1912.06  5576.9 1913.61  5591.8  1912.7
  5606.5 1914.06  5664.1 1914.18  6073.2 1923.26  6108.8 1924.43  6139.7 1927.68
  6205.5 1929.96  6228.6 1929.95  6270.3 1932.98  6282.4 1937.36  6291.8 1938.28
#Mann= 9 ,-1 , 0
  4798.5     .07       0  4876.4     .16       0  5011.7     .07       0
  5030.4     .16       0  5074.1     .07       0    5097     .16       0
  5664.1     .07       0  6073.2     .16       0  6205.5     .07       0
Bank Sta=5011.7,5030.4
XS Rating Curve= 0 ,0
Exp/Cntr=0.3,0.1

Type RM Length L Ch R = 1 ,1577    ,829,829,829
BEGIN DESCRIPTION:
Little Stink Creek 1426
END DESCRIPTION:
XS GIS Cut Line= 4
      1435494.13      6873379.59      1435890.16      6873734.22
      1436354.16      6873772.72      1437010.39       6873531.4
#Sta/Elev= 30
  4002.8 1927.72  4030.8 1926.69  4094.5 1916.56  4143.9 1914.02  4210.5 1913.26
  4292.6 1913.98  4398.8 1913.19    4413  1912.3  4599.5 1911.42  4619.5 1910.15
  4739.9 1912.28  4878.9 1909.86  4930.6 1910.34  4940.6 1909.79  4950.7  1907.7
  4990.8 1908.28  5003.1 1907.39  5011.5 1905.78  5012.6 1904.63  5013.1 1904.13
  5031.8 1904.63  5083.5 1910.73  5088.8 1909.39  5107.4 1912.58  5139.1 1914.24
  5151.1 1913.84  5354.7 1917.67  5430.5 1918.73  5682.8 1925.04  5699.2 1927.06
#Mann= 7 ,-1 , 0
  4002.8     .07       0  4210.5     .16       0  5012.6     .07       0
  5031.8     .16       0  5151.1     .07       0  5354.7     .16       0
  5430.5     .07       0
Bank Sta=5012.6,5031.8
XS Rating Curve= 0 ,0
Exp/Cntr=0.3,0.1

Type RM Length L Ch R = 1 ,748     ,0,0,0
BEGIN DESCRIPTION:
Little Stink Creek 4278
END DESCRIPTION:
XS GIS Cut Line= 4
      1435591.33      6873882.08      1436325.04      6874268.18
      1436481.69      6874346.74      1436768.08       6873933.9
#Sta/Elev= 30
  4170.9 1911.15  4236.9 1910.96  4512.4 1909.66  4547.9 1907.79  4593.1 1906.78
    4661 1908.02  4727.1 1907.94  4785.3 1906.87  4807.9  1904.2    4843 1907.35
  4932.2 1907.84  4941.9 1907.11  4954.3 1901.66  4954.8 1901.16  4973.5 1901.66
  4985.9 1904.22  4991.6 1906.99  4997.2 1908.01  5008.2 1907.42  5080.8 1910.38
  5260.1  1911.6  5373.9 1911.48  5429.3 1911.61  5435.4 1910.95  5441.5  1911.8
  5487.8 1911.93  5521.9 1913.19  5573.4  1913.6  5665.1 1915.03  5677.7 1916.06
#Mann= 8 ,-1 , 0
  4170.9     .16       0  4236.9     .07       0  4954.3     .07       0
  4973.5     .07       0  5260.1     .16       0  5373.9     .07       0
  5487.8     .16       0  5573.4     .07       0
Bank Sta=4954.3,4973.5
XS Rating Curve= 0 ,0
Exp/Cntr=0.3,0.1

Chan Stop Cuts=-1
Use User Specified Reach Order=0
Composite Channel Slope=5