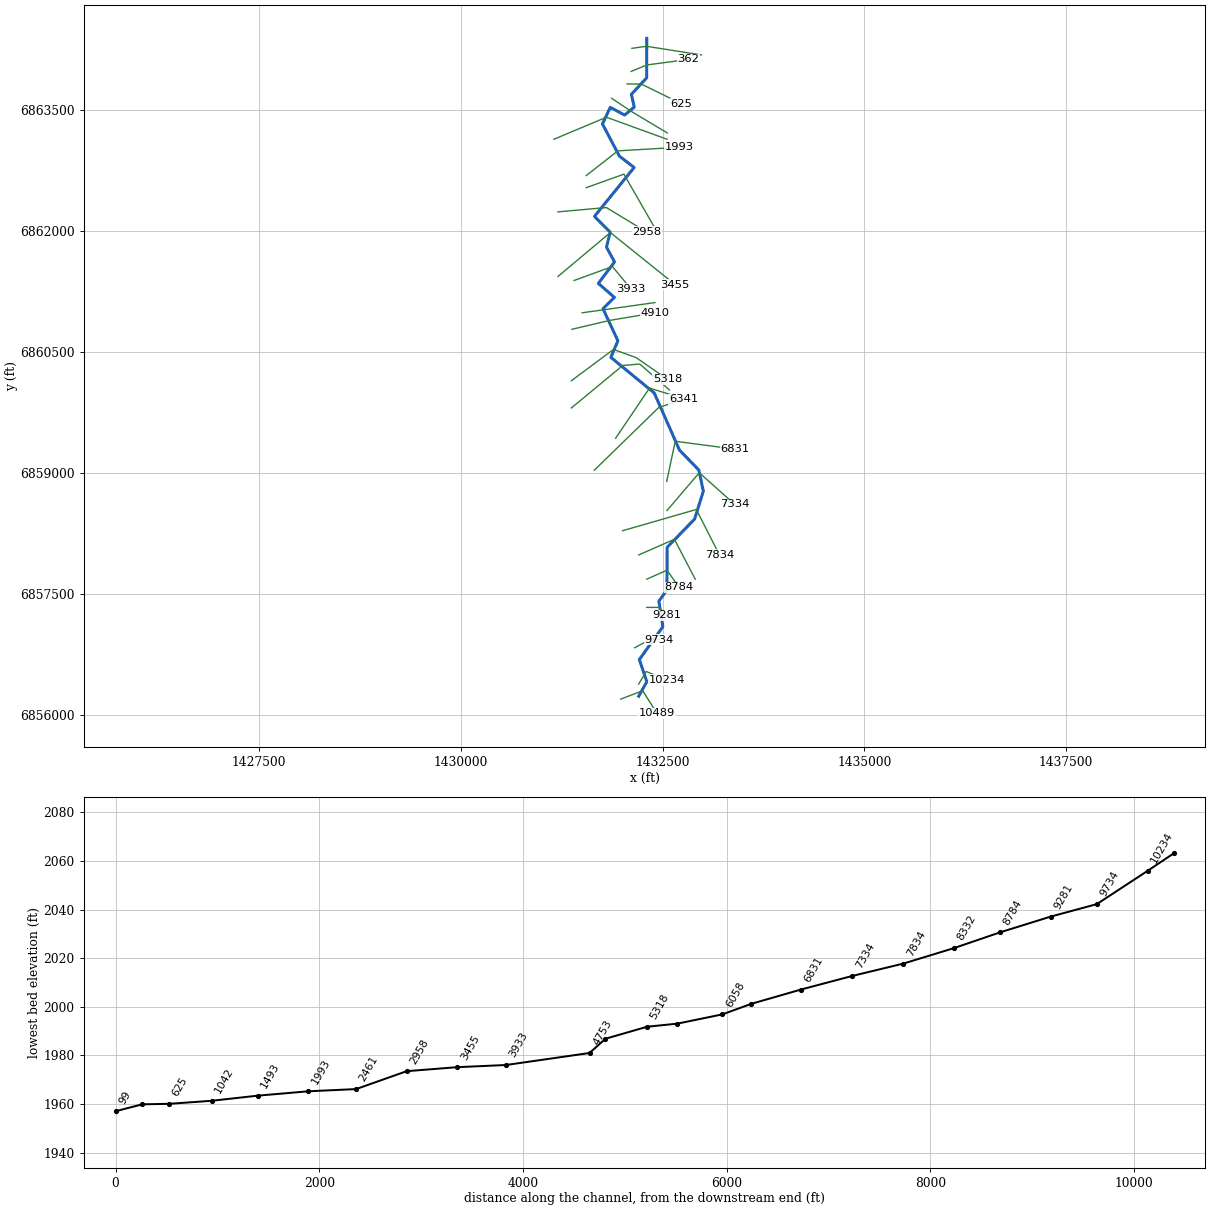
--- Little Stink Creek Trib1.prj (project) ---

Proj Title=Little Stink Creek Trib1 Base Level Engineering
Current Plan=p01
Default Exp/Contr=0.3,0.1
English Units
Geom File=g01
Flow File=f01
Plan File=p01
Y Axis Title=Elevation
X Axis Title(PF)=Main Channel Distance
X Axis Title(XS)=Station
BEGIN DESCRIPTION:
Little Stink Creek Trib1
END DESCRIPTION:
DSS Export Rating Curves= 0
DSS Export Rating Curve Sorted= 0
DSS Export Volume Flow Curves= 0
DXF OffsetX= 0
DXF OffsetY= 0
DXF ScaleX= 1
DXF ScaleY= 10

--- Little Stink Creek Trib1.p01 (plan) ---

Plan Title=Multiple Run
Short Identifier=Multiple
Geom File=g01
Flow File=f01
Subcritical Flow
K Sum by GR= 0
Std Step Tol= 0.01
Critical Tol= 0.01
Num of Std Step Trials= 20
Max Error Tol= 0.3
Flow Tol Ratio= 0.001
Split Flow NTrial= 30
Split Flow Tol= 0.02
Split Flow Ratio= 0.02
Log Output Level= 0
Friction Slope Method= 1
Unsteady Friction Slope Method= 2
Unsteady Bridges Friction Slope Method= 1
Parabolic Critical Depth
Global Vel Dist=  1 , 1 , 1
Global Log Level= 0
CheckData=True
Encroach Param= -1, 0, 0, 0
BEGIN DESCRIPTION:
Multiple Run
END DESCRIPTION:

--- Little Stink Creek Trib1.f01 (steady flow) ---

Flow Title=Multiple
Number of Profiles=7
Profile Names=10-year,25-year,50-year,1pct_min,100-year,1pct_plu,500-year
River Rch & RM= Little Stink Cre,Reach-1,10489
     179     249     308     190     380     758     583
River Rch & RM= Little Stink Cre,Reach-1,6341
     502     740     948     603    1204    2402    1969
River Rch & RM= Little Stink Cre,Reach-1,2958
     649     969    1251     802    1601    3195    2658
River Rch & RM= Little Stink Cre,Reach-1,625
     698    1044    1351     868    1732    3456    2885
Boundary for River Rch & Prof#=Little Stink Cre,Reach-1,1
Up Type=0
Dn Type=3
Dn Slope=0.005
Boundary for River Rch & Prof#=Little Stink Cre,Reach-1,2
Up Type=0
Dn Type=3
Dn Slope=0.005
Boundary for River Rch & Prof#=Little Stink Cre,Reach-1,3
Up Type=0
Dn Type=3
Dn Slope=0.005
Boundary for River Rch & Prof#=Little Stink Cre,Reach-1,4
Up Type=0
Dn Type=3
Dn Slope=0.005
Boundary for River Rch & Prof#=Little Stink Cre,Reach-1,5
Up Type=0
Dn Type=3
Dn Slope=0.005
Boundary for River Rch & Prof#=Little Stink Cre,Reach-1,6
Up Type=0
Dn Type=3
Dn Slope=0.005
Boundary for River Rch & Prof#=Little Stink Cre,Reach-1,7
Up Type=0
Dn Type=3
Dn Slope=0.005

--- Little Stink Creek Trib1.g01 (geometry) ---

Geom Title=Existing Conditions
Program Version=4.10

River Reach=Little Stink Cre,Reach-1
Reach XY= 30
        1432205.        6856238.       1432305.4      6856417.86
      1432212.78       6856691.4      1432504.07      6857098.48
       1432454.8      6857415.35      1432554.46      6857551.86
      1432557.09      6858082.51      1432897.14      6858431.83
      1433005.77      6858777.95      1432949.53      6859040.45
      1432710.83       6859285.7      1432397.16      6859994.18
      1431859.98      6860435.45      1431946.95      6860641.29
      1431762.19      6861038.33      1431903.96      6861178.26
      1431704.98      6861351.93      1431905.37       6861617.8
      1431805.54      6861801.97      1431851.88      6861986.38
      1431656.79      6862182.35      1432148.11        6862788.
      1431965.77       6862928.3      1431755.76      6863327.31
      1431852.43      6863533.05      1432030.01      6863437.41
      1432149.61      6863535.56      1432114.13      6863694.74
      1432303.95      6863898.43        1432305.        6864388.

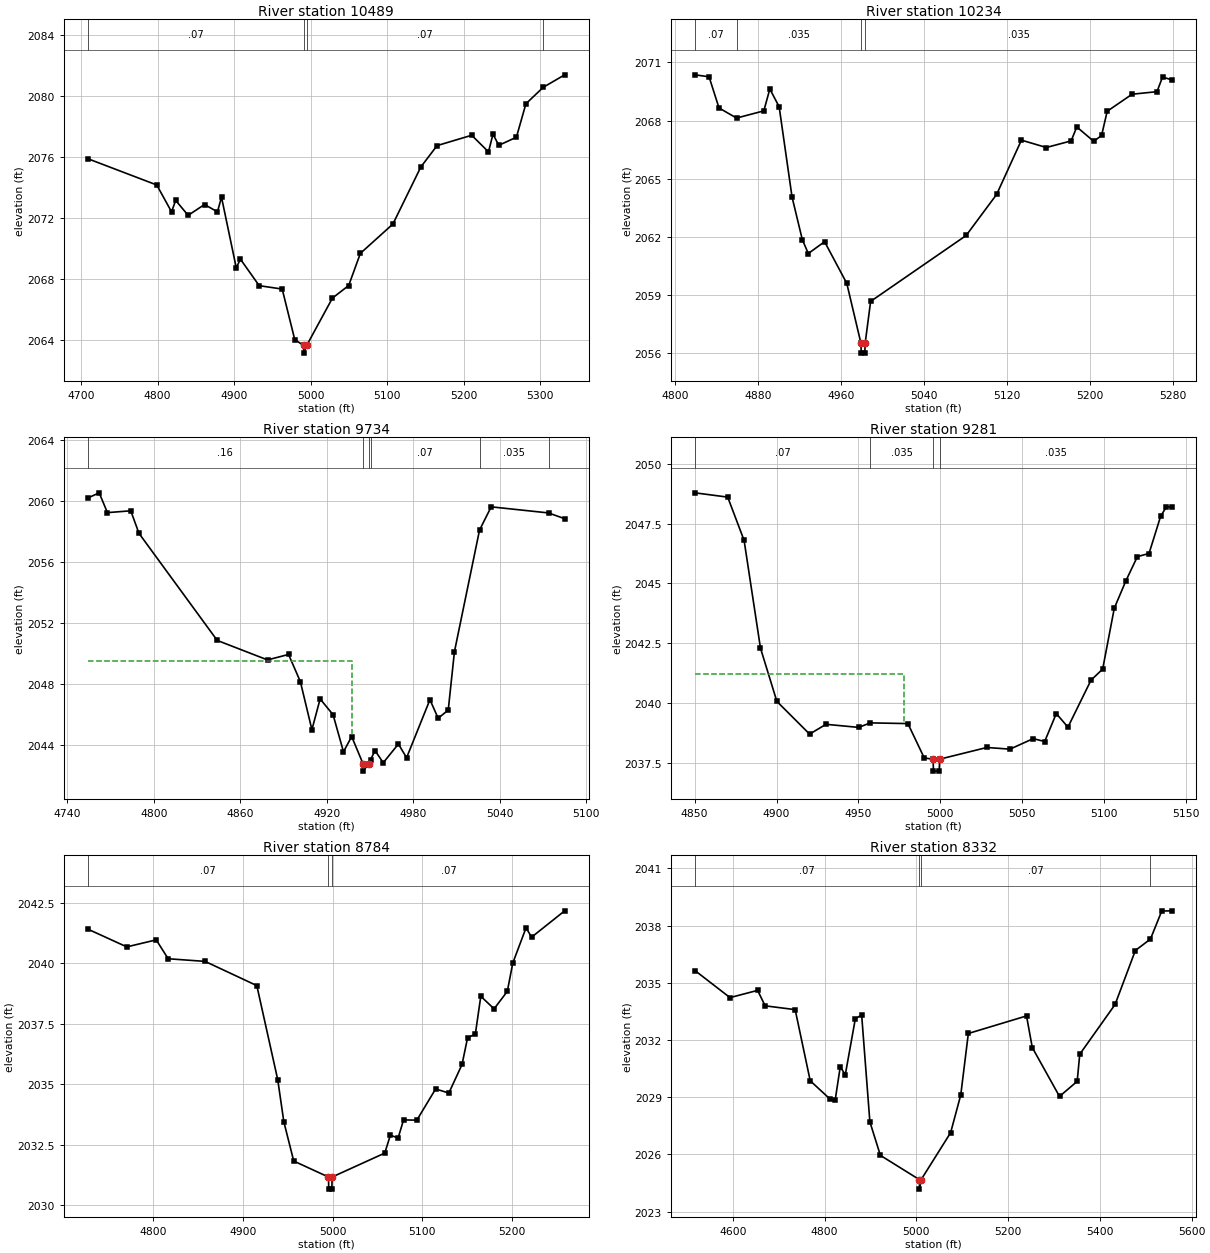
Type RM Length L Ch R = 1 ,10489   ,255,255,255
BEGIN DESCRIPTION:
Little Stink Creek Trib1 4203
END DESCRIPTION:
XS GIS Cut Line= 3
       1431982.3      6856201.71      1432254.33      6856306.46
      1432430.74      6856025.08
#Sta/Elev= 30
  4708.5 2075.91    4799 2074.18  4818.3 2072.42  4823.7 2073.17    4840 2072.19
  4861.4  2072.9  4878.3 2072.42  4883.6 2073.38  4902.9 2068.75  4908.3 2069.32
  4932.9 2067.58  4962.9 2067.36  4979.3 2064.05  4990.9 2063.66  4991.1 2063.16
  4994.9 2063.66  5028.6 2066.77  5049.8 2067.59  5065.1  2069.7  5107.6 2071.62
  5144.1 2075.36  5165.3 2076.76  5210.6 2077.44  5232.5 2076.35  5238.4 2077.51
    5246 2076.78    5269 2077.31  5281.4  2079.5    5304 2080.58  5332.1  2081.4
#Mann= 4 ,-1 , 0
  4708.5     .07       0  4990.9     .07       0  4994.9     .07       0
    5304     .16       0
Bank Sta=4990.9,4994.9
XS Rating Curve= 0 ,0
Exp/Cntr=0.3,0.1

Type RM Length L Ch R = 1 ,10234   ,500,500,500
BEGIN DESCRIPTION:
Little Stink Creek Trib1 16.0
END DESCRIPTION:
XS GIS Cut Line= 3
      1432205.01      6856388.02      1432296.91      6856544.07
      1432554.96      6856438.01
#Sta/Elev= 30
  4818.9 2070.36  4832.5 2070.26  4842.1 2068.65    4859 2068.13  4885.3  2068.5
  4891.1 2069.63  4900.1 2068.71  4912.5 2064.06  4922.4 2061.86  4928.2 2061.14
  4943.9 2061.75  4965.3  2059.6    4979  2056.5  4979.2    2056  4982.7    2056
    4983  2056.5  4988.3 2058.67  5080.4 2062.07  5109.8 2064.19  5133.7 2066.99
  5157.7 2066.61  5181.6 2066.95  5187.1 2067.67  5203.4 2066.93    5211 2067.23
  5216.4 2068.48  5240.4 2069.36  5264.4 2069.49  5269.8 2070.25    5279 2070.09
#Mann= 4 ,-1 , 0
  4818.9     .07       0    4859    .035       0    4979    .035       0
    4983    .035       0
Bank Sta=4979,4983
XS Rating Curve= 0 ,0
Exp/Cntr=0.3,0.1

Type RM Length L Ch R = 1 ,9734    ,453,453,453
BEGIN DESCRIPTION:
Little Stink Creek Trib1 15.0
END DESCRIPTION:
XS GIS Cut Line= 3
      1432155.01      6856838.01      1432371.57      6856954.71
      1432455.01        6856938.
#Sta/Elev= 30
    4754  2060.2  4762.1 2060.55  4767.8 2059.25    4784 2059.37  4789.7 2057.89
    4844 2050.86  4878.9 2049.58  4893.5 2049.94  4901.7 2048.15  4909.7    2045
  4915.4 2047.02  4924.4 2045.98  4931.6 2043.55  4937.3 2044.55  4945.1 2042.78
  4945.3 2042.28  4949.1 2042.78  4950.4 2043.03  4953.5 2043.63  4959.2 2042.83
  4969.7 2044.06  4975.4 2043.16  4991.6 2046.97  4997.3 2045.75  5004.3 2046.29
  5008.6 2050.12    5026  2058.1  5034.1 2059.63  5073.9 2059.23  5085.1 2058.85
#Mann= 6 ,-1 , 0
    4754     .16       0  4945.1     .07       0  4949.1     .16       0
  4950.4     .07       0    5026    .035       0  5073.9     .07       0
#XS Ineff= 2 , 0
         4937.26 2049.52
Permanent Ineff=
       F       F
Bank Sta=4945.1,4949.1
XS Rating Curve= 0 ,0
Exp/Cntr=0.3,0.1

Type RM Length L Ch R = 1 ,9281    ,497,497,497
BEGIN DESCRIPTION:
Little Stink Creek Trib1 14.0
END DESCRIPTION:
XS GIS Cut Line= 3
      1432305.05        6857338.      1432454.85        6857338.
      1432554.98      6857238.02
#Sta/Elev= 30
  4850.2 2048.79  4870.2 2048.61  4880.2  2046.8  4890.2 2042.29  4900.2 2040.06
  4920.2 2038.69  4930.2  2039.1  4950.2 2038.97  4957.2 2039.16  4980.2 2039.13
  4990.2 2037.69  4995.6 2037.64  4995.8 2037.14  4999.3 2037.14  4999.6 2037.64
  5028.4 2038.13  5042.5 2038.06  5056.7  2038.5  5063.7 2038.38  5070.8 2039.55
  5077.9 2038.98    5092 2040.95  5099.1 2041.41  5106.2 2043.96  5113.3 2045.11
  5120.3 2046.12  5127.4 2046.25  5134.5 2047.81    5138  2048.2  5141.5  2048.2
#Mann= 4 ,-1 , 0
  4850.2     .07       0  4957.2    .035       0  4995.6    .035       0
  4999.6    .035       0
#XS Ineff= 2 , 0
         4977.92 2041.21
Permanent Ineff=
       F       F
Bank Sta=4995.6,4999.6
XS Rating Curve= 0 ,0
Exp/Cntr=0.3,0.1

Type RM Length L Ch R = 1 ,8784    ,452,452,452
BEGIN DESCRIPTION:
Little Stink Creek Trib1 13.0
END DESCRIPTION:
XS GIS Cut Line= 3
        1432305.        6857688.      1432554.55      6857798.19
      1432705.01      6857587.99
#Sta/Elev= 30
  4727.2 2041.41  4770.9 2040.67  4803.7 2040.96    4817 2040.18  4858.1 2040.07
  4915.7 2039.07    4939 2035.18  4945.8 2033.44  4956.8 2031.82  4995.5 2031.16
  4995.8 2030.66  4999.3 2030.66  4999.5 2031.16  5058.2 2032.15  5064.4 2032.89
    5073 2032.77  5079.1 2033.52  5093.9 2033.51  5114.8  2034.8  5129.5 2034.63
  5144.2 2035.81  5150.4 2036.92    5159 2037.06  5165.1 2038.63  5179.9 2038.11
  5194.6 2038.83  5200.7    2040  5215.5 2041.46  5221.6 2041.07  5258.5 2042.16
#Mann= 3 ,-1 , 0
  4727.2     .07       0  4995.5     .07       0  4999.5     .07       0
Bank Sta=4995.5,4999.5
XS Rating Curve= 0 ,0
Exp/Cntr=0.3,0.1

Type RM Length L Ch R = 1 ,8332    ,498,498,498
BEGIN DESCRIPTION:
Little Stink Creek Trib1 12.0
END DESCRIPTION:
XS GIS Cut Line= 3
      1432205.02      6857988.01      1432646.81      6858181.98
      1432905.01      6857687.98
#Sta/Elev= 30
  4517.5 2035.64  4593.9 2034.22  4654.1  2034.6  4670.4 2033.79  4735.9 2033.59
  4768.7 2029.86  4812.4 2028.89  4823.1 2028.85  4834.2  2030.6  4845.1 2030.17
    4867 2033.11  4880.8 2033.31  4898.7 2027.71  4921.6 2025.95  5006.5 2024.68
  5006.8 2024.18  5010.5 2024.68  5074.7 2027.14  5096.8 2029.12  5113.3 2032.34
  5240.1 2033.26  5252.7  2031.6    5312 2029.04  5350.5 2029.83  5356.1 2031.25
  5433.1 2033.86  5477.3 2036.69  5510.2 2037.29  5534.8 2038.76  5557.4 2038.77
#Mann= 4 ,-1 , 0
  4517.5     .07       0  5006.5     .07       0  5010.5     .07       0
  5510.2    .035       0
Bank Sta=5006.5,5010.5
XS Rating Curve= 0 ,0
Exp/Cntr=0.3,0.1

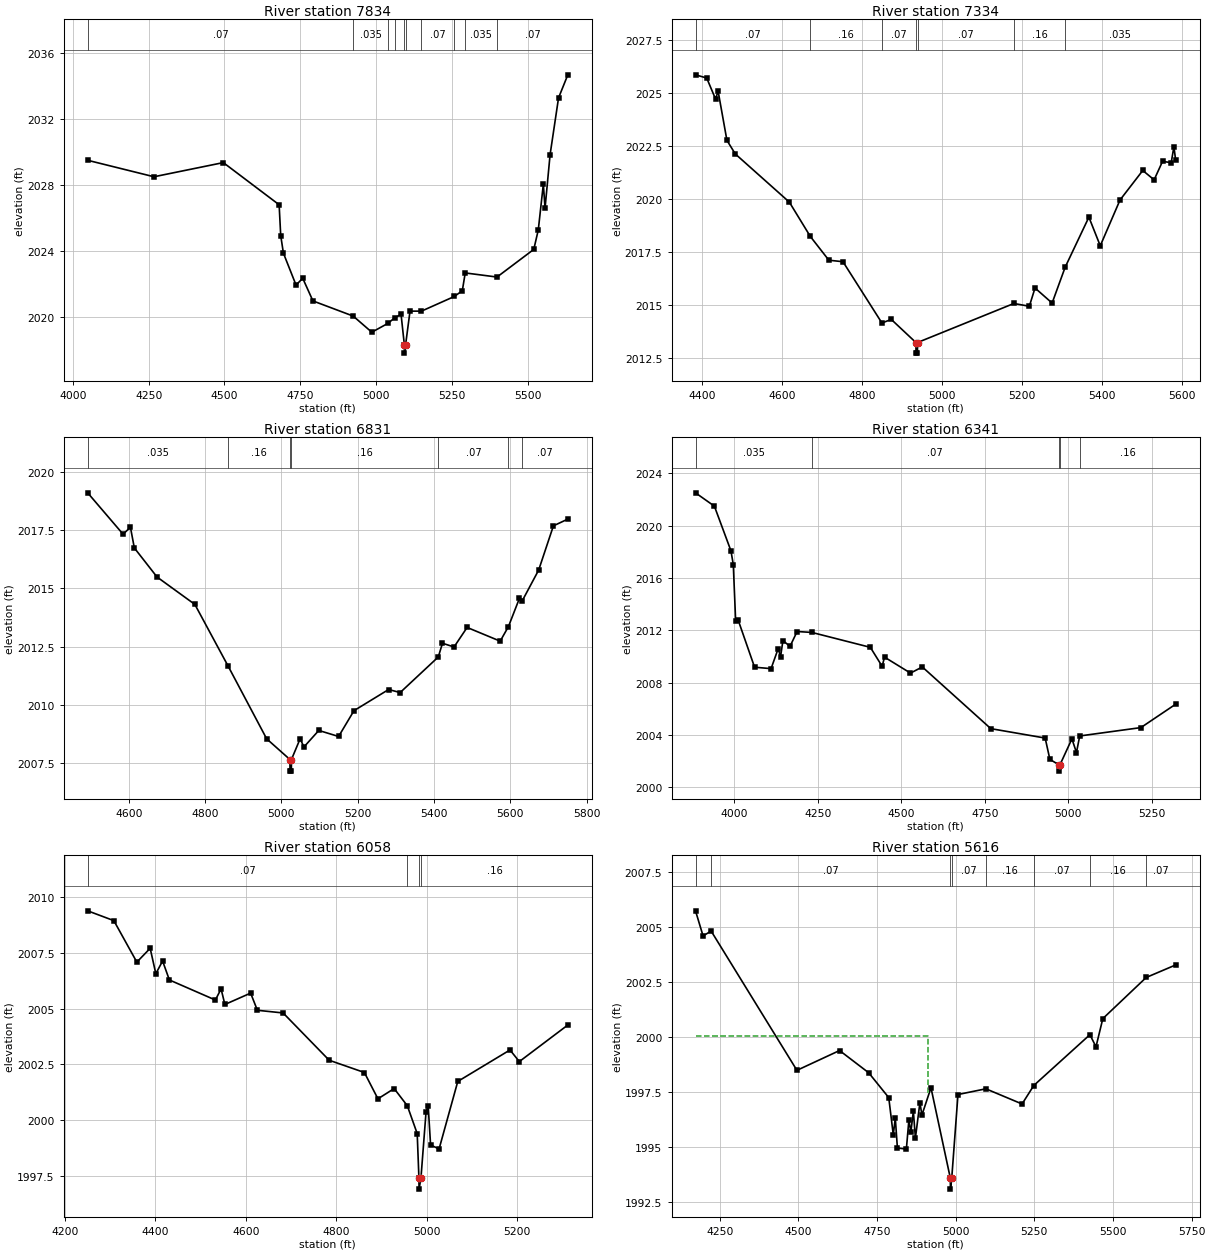
Type RM Length L Ch R = 1 ,7834    ,500,500,500
BEGIN DESCRIPTION:
Little Stink Creek Trib1 11.0
END DESCRIPTION:
XS GIS Cut Line= 3
      1432004.95      6858287.99      1432918.82      6858551.13
      1433205.01      6857987.98
#Sta/Elev= 30
    4049 2029.51  4267.6 2028.51  4496.1 2029.37  4680.1 2026.81  4685.3 2024.94
  4694.2 2023.87  4735.9 2021.93  4757.8 2022.35  4791.5 2020.97  4924.2 2020.05
  4985.6 2019.07    5039 2019.61    5062 2019.96    5082 2020.15  5092.9  2018.3
  5093.1  2017.8  5096.9  2018.3  5111.5 2020.35  5149.3 2020.35  5257.6 2021.24
  5283.9 2021.59  5293.5 2022.67  5398.3 2022.42  5519.5  2024.1  5534.3 2025.28
    5551 2028.06  5556.6  2026.6  5573.2 2029.85  5601.1  2033.3  5631.7  2034.7
#Mann= 10 ,-1 , 0
    4049     .07       0  4924.2    .035       0    5039     .07       0
    5062    .035       0  5092.9    .035       0  5096.9    .035       0
  5149.3     .07       0  5257.6     .16       0  5293.5    .035       0
  5398.3     .07       0
Bank Sta=5092.9,5096.9
XS Rating Curve= 0 ,0
Exp/Cntr=0.3,0.1

Type RM Length L Ch R = 1 ,7334    ,503,503,503
BEGIN DESCRIPTION:
Little Stink Creek Trib1 10.0
END DESCRIPTION:
XS GIS Cut Line= 3
        1432555.        6858538.      1432955.43      6859006.36
      1433390.54      6858617.58
#Sta/Elev= 30
  4383.8 2025.85  4411.8  2025.7  4433.8 2024.71  4440.3 2025.08  4462.3 2022.76
  4483.2 2022.12  4618.2 2019.85  4670.7 2018.23    4717 2017.11  4752.2 2017.04
  4849.6 2014.15  4872.9 2014.32  4934.5 2013.23  4934.8 2012.73  4938.3 2012.73
  4938.5 2013.23  5179.2 2015.07  5217.9 2014.94  5232.1  2015.8  5274.8 2015.09
  5307.4 2016.78  5366.7 2019.14  5395.1 2017.79  5444.5 2019.95  5501.3 2021.34
  5529.7  2020.9  5550.7 2021.77  5572.4 2021.71  5579.1 2022.46  5583.5 2021.83
#Mann= 7 ,-1 , 0
  4383.8     .07       0  4670.7     .16       0  4849.6     .07       0
  4934.5     .07       0  4938.5     .07       0  5179.2     .16       0
  5307.4    .035       0
Bank Sta=4934.5,4938.5
XS Rating Curve= 0 ,0
Exp/Cntr=0.3,0.1

Type RM Length L Ch R = 1 ,6831    ,490,490,490
BEGIN DESCRIPTION:
Little Stink Creek Trib1 9.0
END DESCRIPTION:
XS GIS Cut Line= 3
      1432551.52      6858898.38       1432657.3      6859396.09
      1433400.79      6859298.51
#Sta/Elev= 30
  4492.2 2019.11    4585 2017.33  4604.3 2017.63  4614.5 2016.74    4674 2015.49
  4773.2 2014.31  4860.6 2011.65  4961.4 2008.53  5022.4 2007.64  5022.6 2007.14
  5026.1 2007.14  5026.4 2007.64  5049.1 2008.53  5059.2 2008.18  5098.1 2008.89
    5150 2008.63  5190.3 2009.74  5281.1 2010.65  5311.4 2010.52  5411.3 2012.05
  5422.3 2012.64  5452.6 2012.48  5486.9 2013.32  5573.6 2012.73  5595.3 2013.36
    5624 2014.57  5630.6 2014.44  5674.5 2015.79  5713.1 2017.69  5750.9 2017.98
#Mann= 7 ,-1 , 0
  4492.2    .035       0  4860.6     .16       0  5022.4     .07       0
  5026.4     .16       0  5411.3     .07       0  5595.3     .16       0
  5630.6     .07       0
Bank Sta=5022.4,5026.4
XS Rating Curve= 0 ,0
Exp/Cntr=0.3,0.1

Type RM Length L Ch R = 1 ,6341    ,283,283,283
BEGIN DESCRIPTION:
Little Stink Creek Trib1 8.0
END DESCRIPTION:
XS GIS Cut Line= 3
        1431655.        6859038.      1432454.52      6859816.16
 1432760.68380416859914.30146481
#Sta/Elev= 30
  3884.3 2022.52  3940.8  2021.5  3990.4 2018.08  3997.4 2017.03  4004.5 2012.68
  4011.5 2012.82  4061.1 2009.18  4110.5 2009.07  4131.9 2010.61  4138.8 2009.97
    4146 2011.22  4167.1 2010.77  4188.4 2011.91  4232.6 2011.84  4407.6  2010.7
  4442.9 2009.25  4450.1 2009.95  4527.8 2008.73  4563.2  2009.2  4768.2 2004.48
  4930.9 2003.76    4945 2002.13    4971 2001.73  4971.3 2001.23  4975.5 2001.73
    5011  2003.7  5024.6 2002.65  5034.3 2003.92  5217.4 2004.56 5321.51 2006.35
#Mann= 5 ,-1 , 0
  3884.3    .035       0  4232.6     .07       0    4971     .07       0
  4975.5     .07       0  5034.3     .16       0
Bank Sta=4971,4975.5
XS Rating Curve= 0 ,0
Exp/Cntr=0.3,0.1

Type RM Length L Ch R = 1 ,6058    ,442,442,442
BEGIN DESCRIPTION:
Little Stink Creek Trib1 4125
END DESCRIPTION:
XS GIS Cut Line= 3
      1431918.69       6859433.4      1432338.43      6860054.71
      1432637.38      6859962.99
#Sta/Elev= 30
  4250.2 2009.39  4308.1 2008.95    4359 2007.09  4388.5 2007.71    4401 2006.57
    4416 2007.14    4431 2006.29  4532.8 2005.39  4545.4 2005.89  4553.8 2005.19
  4610.8  2005.7  4625.7 2004.93  4682.7 2004.81  4784.6 2002.69  4862.5 2002.14
  4892.5 2000.96  4928.4 2001.42  4957.5 2000.65  4979.4  1999.4  4983.2 1997.41
  4983.5 1996.91  4987.7 1997.41    4999 2000.38  5003.7 2000.64    5009 1998.89
  5027.8 1998.71  5069.2 2001.74  5184.7 2003.15  5205.4 2002.63  5312.7 2004.27
#Mann= 4 ,-1 , 0
  4250.2     .07       0  4957.5     .16       0  4983.2     .07       0
  4987.7     .16       0
Bank Sta=4983.2,4987.7
XS Rating Curve= 0 ,0
Exp/Cntr=0.3,0.1

Type RM Length L Ch R = 1 ,5616    ,298,298,298
BEGIN DESCRIPTION:
Little Stink Creek Trib1 7.1
END DESCRIPTION:
XS GIS Cut Line= 4
       1431370.5      6859808.54      1432007.66      6860335.28
        1432218.      6860352.93      1432585.71      6860031.91
#Sta/Elev= 30
  4173.3 2005.74  4197.3  2004.6    4223 2004.82  4495.6 1998.49  4631.1 1999.39
  4723.6 1998.38  4787.4 1997.25  4801.8 1995.56  4808.2 1996.32  4814.9 1994.96
  4843.4 1994.91  4851.3 1996.22  4857.7 1995.69  4865.6 1996.63  4872.1 1995.41
  4886.4 1997.02  4892.9 1996.46  4921.6  1997.7  4983.1 1993.59  4983.4 1993.09
  4987.6 1993.59  5007.4 1997.39    5096 1997.65  5211.1 1996.96  5248.3  1997.8
  5426.7 2000.11    5446 1999.56  5467.7 2000.84  5605.5 2002.71  5699.2 2003.28
#Mann= 8 ,-1 , 0
  4173.3    .035       0    4223     .07       0  4983.1     .07       0
  4987.6     .07       0    5096     .16       0  5248.3     .07       0
  5426.7     .16       0  5605.5     .07       0
#XS Ineff= 2 , 0
         4913.71 2000.04
Permanent Ineff=
       F       F
Bank Sta=4983.1,4987.6
XS Rating Curve= 0 ,0
Exp/Cntr=0.3,0.1

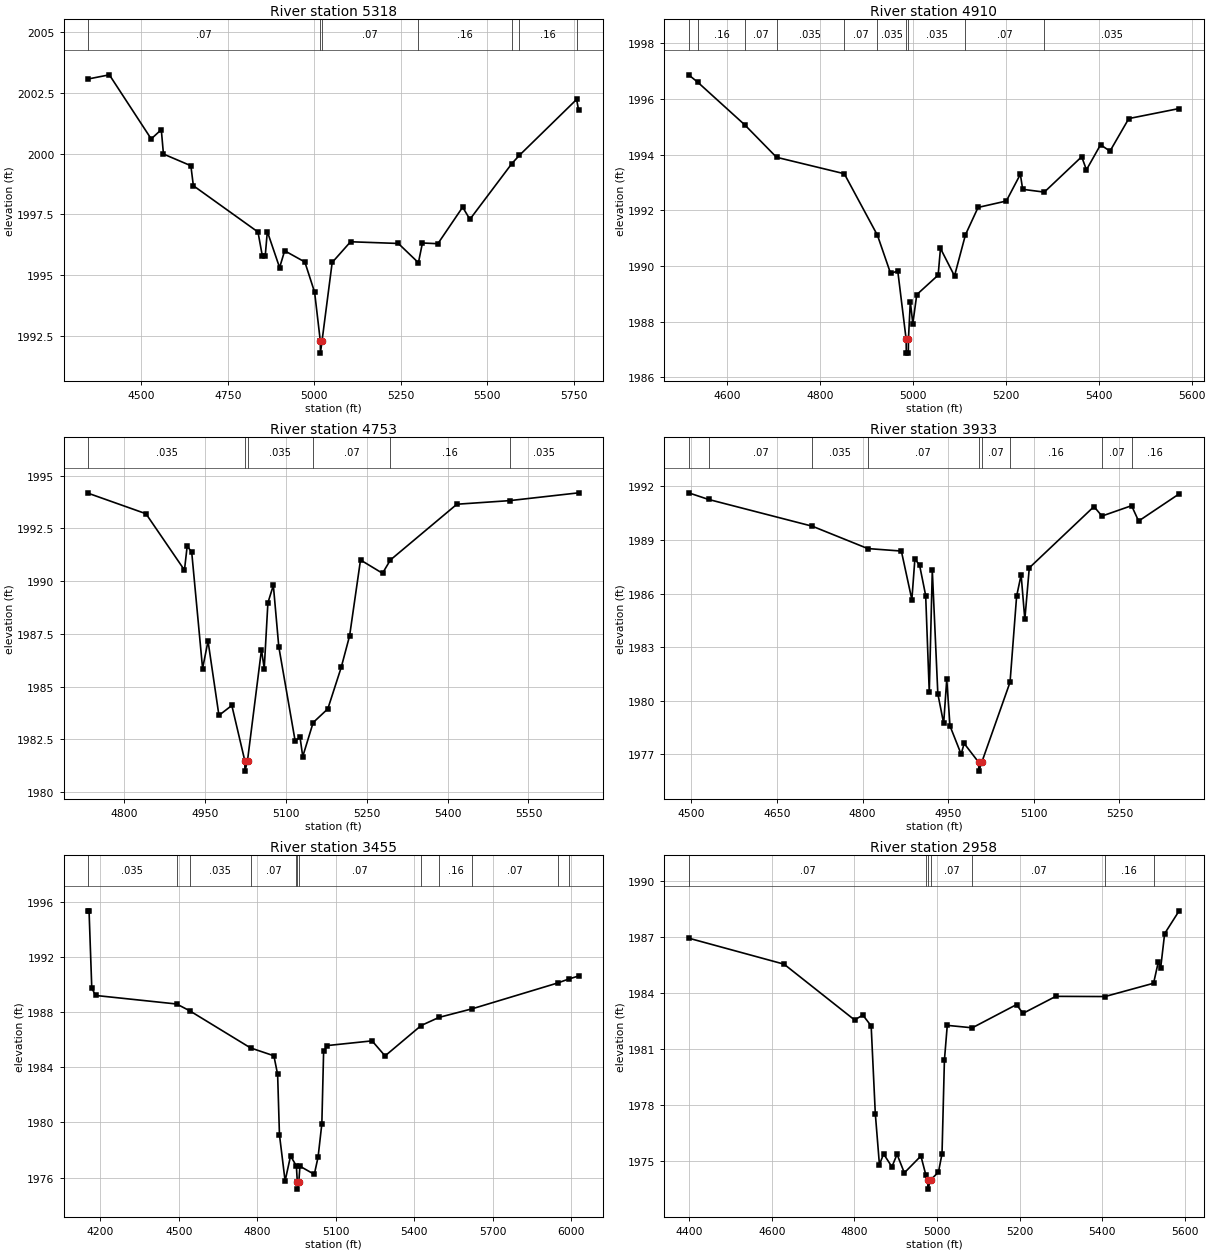
Type RM Length L Ch R = 1 ,5318    ,408,408,408
BEGIN DESCRIPTION:
Little Stink Creek Trib1 4123
END DESCRIPTION:
XS GIS Cut Line= 4
      1431370.93      6860146.46      1431892.17      6860533.79
      1432170.87      6860433.52       1432560.1      6860165.28
#Sta/Elev= 30
  4345.9 2003.06  4407.1 2003.23  4528.1  2000.6  4557.3 2000.98  4563.5 1999.98
  4642.8  1999.5    4650 1998.68  4836.9 1996.78  4849.3 1995.81  4857.7 1995.78
  4863.9  1996.8  4899.4 1995.32    4914 1996.01  4972.4 1995.55  5000.6 1994.31
  5017.1 1992.31  5017.4 1991.81  5022.1 1992.31  5051.4 1995.53  5104.6 1996.38
  5242.7 1996.31  5300.8 1995.52  5312.4 1996.33    5357  1996.3  5428.7  1997.8
  5449.7  1997.3  5571.1 1999.59  5592.3 1999.92  5758.2 2002.22  5764.2 2001.77
#Mann= 7 ,-1 , 0
  4345.9     .07       0  5017.1     .07       0  5022.1     .07       0
  5300.8     .16       0  5571.1     .07       0  5592.3     .16       0
  5758.2     .07       0
Bank Sta=5017.1,5022.1
XS Rating Curve= 0 ,0
Exp/Cntr=0.3,0.1

Type RM Length L Ch R = 1 ,4910    ,157,157,157
BEGIN DESCRIPTION:
Little Stink Creek Trib1 7.0
END DESCRIPTION:
XS GIS Cut Line= 3
      1431377.04      6860783.29      1431846.57      6860893.94
      1432411.78      6860988.73
#Sta/Elev= 30
  4517.6 1996.86  4537.5 1996.59  4638.6 1995.06  4706.7  1993.9  4852.5 1993.31
  4923.9  1991.1  4952.2 1989.73  4967.6 1989.82  4985.6 1987.37    4986 1986.87
  4990.3 1986.87  4990.6 1987.37  4994.6 1988.72    5000 1987.93  5008.5 1988.97
  5054.5 1989.67  5059.5 1990.63  5089.7 1989.64  5113.3 1991.12  5140.4  1992.1
  5201.2 1992.33  5231.4 1993.29  5236.4 1992.75    5283 1992.65  5363.4 1993.92
  5373.6 1993.45    5404 1994.35  5424.3 1994.12  5464.8 1995.29  5573.1 1995.65
#Mann= 10 ,-1 , 0
  4517.6     .07       0  4537.5     .16       0  4638.6     .07       0
  4706.7    .035       0  4852.5     .07       0  4923.9    .035       0
  4985.6    .035       0  4990.6    .035       0  5113.3     .07       0
    5283    .035       0
Bank Sta=4985.6,4990.6
XS Rating Curve= 0 ,0
Exp/Cntr=0.3,0.1

Type RM Length L Ch R = 1 ,4753    ,820,820,820
BEGIN DESCRIPTION:
Little Stink Creek Trib1 6.0
END DESCRIPTION:
XS GIS Cut Line= 3
      1431504.99        6860988.      1431768.71      6861024.93
      1432405.61        6861114.
#Sta/Elev= 30
  4733.7 1994.16  4840.8 1993.19  4912.2 1990.52  4917.2 1991.65  4925.6 1991.38
  4945.8 1985.86  4955.9 1987.16  4976.1 1983.64    5000 1984.11    5024  1981.5
  5024.4    1981  5029.1  1981.5    5055 1986.75  5060.1 1985.86  5066.9 1988.97
    5077  1989.8  5087.1 1986.89  5117.4 1982.43  5126.5  1982.6  5131.5 1981.69
  5150.8  1983.3    5178 1983.95  5202.9 1985.92  5218.4 1987.41  5238.6    1991
  5279.4 1990.37    5294    1991  5417.3 1993.64  5514.9 1993.81  5643.1 1994.18
#Mann= 6 ,-1 , 0
  4733.7    .035       0    5024    .035       0  5029.1    .035       0
  5150.8     .07       0    5294     .16       0  5514.9    .035       0
Bank Sta=5024,5029.1
XS Rating Curve= 0 ,0
Exp/Cntr=0.3,0.1

Type RM Length L Ch R = 1 ,3933    ,478,478,478
BEGIN DESCRIPTION:
Little Stink Creek Trib1 5.0
END DESCRIPTION:
XS GIS Cut Line= 3
      1431405.01        6861388.      1431878.96      6861561.18
      1432105.02      6861287.98
#Sta/Elev= 30
  4495.4 1991.64  4530.2 1991.27  4712.1 1989.77  4809.1 1988.52    4868 1988.38
  4886.4 1985.66  4891.7 1987.94    4900 1987.58  4910.6 1985.89  4916.9 1980.47
  4922.2 1987.31  4931.9 1980.39  4942.1 1978.73  4947.5 1981.19  4953.2 1978.59
  4972.7 1977.01    4978 1977.61  5003.3 1976.56  5003.8 1976.06  5008.9 1976.56
  5058.4 1981.04  5069.9 1985.85  5077.8 1987.05  5084.3 1984.55  5092.1 1987.44
  5205.4 1990.87  5219.4 1990.34  5271.3 1990.92  5283.6 1990.06  5354.6 1991.58
#Mann= 9 ,-1 , 0
  4495.4    .035       0  4530.2     .07       0  4712.1    .035       0
  4809.1     .07       0  5003.3     .07       0  5008.9     .07       0
  5058.4     .16       0  5219.4     .07       0  5271.3     .16       0
Bank Sta=5003.3,5008.9
XS Rating Curve= 0 ,0
Exp/Cntr=0.3,0.1

Type RM Length L Ch R = 1 ,3455    ,497,497,497
BEGIN DESCRIPTION:
Little Stink Creek Trib1 4.0
END DESCRIPTION:
XS GIS Cut Line= 3
      1431204.96      6861437.97      1431853.39      6861981.98
      1432654.96      6861338.03
#Sta/Elev= 30
  4153.6 1995.33  4156.9 1995.33  4167.3 1989.74  4181.6  1989.2  4491.8 1988.58
  4541.5 1988.09    4774  1985.4  4863.3 1984.83  4877.6 1983.48  4884.6 1979.11
  4906.2 1975.76  4927.1 1977.58  4949.3 1976.84  4952.9 1975.67  4953.3 1975.17
  4958.5 1975.67  4962.9 1976.83  5017.8 1976.24  5032.2 1977.49  5046.6  1979.9
  5053.4 1985.15  5067.4 1985.57  5238.6 1985.91  5288.2 1984.82  5426.1 1987.02
  5494.3 1987.61  5622.3 1988.24  5949.2 1990.11  5990.2 1990.39  6028.2 1990.61
#Mann= 12 ,-1 , 0
  4153.6    .035       0  4491.8     .07       0  4541.5    .035       0
    4774     .07       0  4949.3     .16       0  4952.9     .07       0
  4958.5     .07       0  5426.1     .07       0  5494.3     .16       0
  5622.3     .07       0  5949.2    .035       0  5990.2     .07       0
Bank Sta=4952.9,4958.5
XS Rating Curve= 0 ,0
Exp/Cntr=0.3,0.1

Type RM Length L Ch R = 1 ,2958    ,497,497,497
BEGIN DESCRIPTION:
Little Stink Creek Trib1 3.0
END DESCRIPTION:
XS GIS Cut Line= 3
      1431205.02        6862238.       1431803.6      6862291.87
        1432305.        6861988.
#Sta/Elev= 30
    4399 1986.93  4629.9 1985.54  4800.6 1982.56  4820.7 1982.82  4840.8 1982.24
  4850.8 1977.56  4860.8 1974.83  4870.9  1975.4    4891 1974.71  4903.5 1975.38
  4921.1 1974.39  4961.2 1975.29  4973.5 1974.25  4977.6 1974.02  4978.1 1973.52
    4985 1974.02  5003.7 1974.43  5012.3 1975.41  5018.1  1980.4    5025 1982.27
  5085.6 1982.14  5192.7 1983.38  5208.2 1982.91  5287.7 1983.82  5406.8 1983.81
  5524.4 1984.52  5535.9 1985.66  5541.7 1985.36  5551.2 1987.17  5586.3 1988.39
#Mann= 7 ,-1 , 0
    4399     .07       0  4973.5     .16       0  4977.6     .07       0
    4985     .07       0  5085.6     .07       0  5406.8     .16       0
  5524.4     .07       0
Bank Sta=4977.6,4985
XS Rating Curve= 0 ,0
Exp/Cntr=0.3,0.1

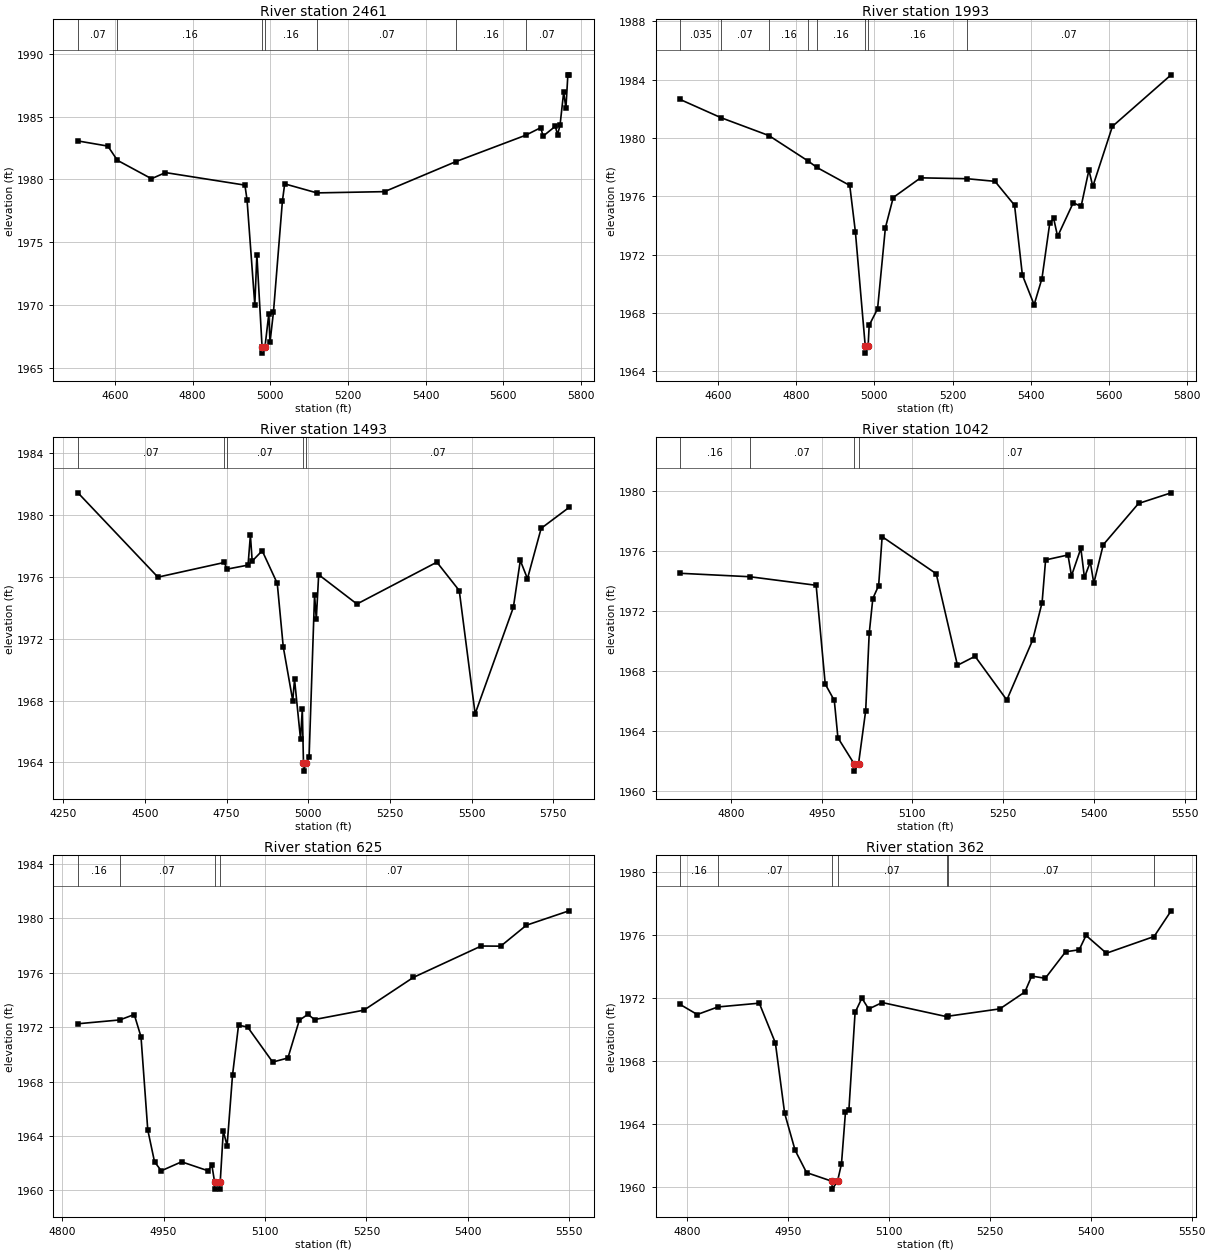
Type RM Length L Ch R = 1 ,2461    ,468,468,468
BEGIN DESCRIPTION:
Little Stink Creek Trib1 2.0
END DESCRIPTION:
XS GIS Cut Line= 3
      1431554.95      6862537.98      1432021.43      6862705.08
        1432405.      6862037.99
#Sta/Elev= 30
  4504.5 1983.06  4581.5 1982.65    4606 1981.52  4693.9 1980.05  4729.9 1980.54
  4934.6 1979.54  4940.1 1978.36  4960.1 1969.99  4965.4    1974  4978.8 1966.65
  4979.3 1966.15  4986.3 1966.65  4996.2 1969.29  4999.2    1967  5008.2 1969.44
  5031.2 1978.27  5037.1 1979.64  5120.1 1978.92  5294.4 1979.02  5478.6 1981.42
  5657.5 1983.51  5696.9 1984.12  5702.7 1983.44  5734.3 1984.23    5740 1983.56
  5746.4 1984.31  5755.8 1986.94  5761.6 1985.67  5766.6 1988.33  5769.5 1988.33
#Mann= 7 ,-1 , 0
  4504.5     .07       0    4606     .16       0  4978.8     .07       0
  4986.3     .16       0  5120.1     .07       0  5478.6     .16       0
  5657.5     .07       0
Bank Sta=4978.8,4986.3
XS Rating Curve= 0 ,0
Exp/Cntr=0.3,0.1

Type RM Length L Ch R = 1 ,1993    ,500,500,500
BEGIN DESCRIPTION:
Little Stink Creek Trib1 1.0
END DESCRIPTION:
XS GIS Cut Line= 3
      1431554.98      6862687.99      1431946.82      6862994.04
      1432705.05        6863038.
#Sta/Elev= 30
  4502.8 1982.65  4607.3  1981.4  4730.2 1980.17  4830.7 1978.42  4853.1 1977.98
    4937 1976.75  4951.4 1973.57  4976.6 1965.74  4977.1 1965.24  4984.1 1965.74
  4986.7 1967.15  5008.2 1968.28  5028.2 1973.84  5048.3 1975.92  5118.4 1977.27
  5237.2 1977.21  5308.7 1977.03  5358.8 1975.39  5378.8  1970.6  5408.9 1968.56
  5428.9 1970.36  5448.9 1974.16  5458.9 1974.48    5469 1973.25    5509 1975.56
  5529.1 1975.31  5549.1  1977.8  5559.1 1976.68  5609.2  1980.8  5759.5 1984.34
#Mann= 8 ,-1 , 0
  4502.8    .035       0  4607.3     .07       0  4730.2     .16       0
  4830.7     .07       0  4853.1     .16       0  4976.6     .07       0
  4984.1     .16       0  5237.2     .07       0
Bank Sta=4976.6,4984.1
XS Rating Curve= 0 ,0
Exp/Cntr=0.3,0.1

Type RM Length L Ch R = 1 ,1493    ,451,451,451
BEGIN DESCRIPTION:
Little Stink Creek Trib1 0.1
END DESCRIPTION:
XS GIS Cut Line= 3
      1431155.01        6863138.      1431804.89      6863410.77
      1432555.03      6863137.99
#Sta/Elev= 30
  4295.2 1981.45  4539.9 1975.99    4743 1976.94  4751.6 1976.51  4815.8 1976.77
    4823 1978.71  4828.5 1977.03  4859.1  1977.7  4905.2 1975.59  4923.5 1971.49
  4952.7 1967.99  4958.1 1969.38  4976.5 1965.49  4981.9 1967.45  4985.5 1963.93
    4986 1963.43    4993 1963.93  5002.7 1964.36  5019.4 1974.85  5024.7 1973.27
    5032 1976.15  5149.1 1974.25  5393.8 1976.96  5462.3 1975.12  5510.9 1967.14
  5627.9 1974.03  5649.2 1977.07  5671.1 1975.89    5713 1979.15  5798.2  1980.5
#Mann= 5 ,-1 , 0
  4295.2     .07       0    4743     .16       0  4751.6     .07       0
  4985.5     .07       0    4993     .07       0
Bank Sta=4985.5,4993
XS Rating Curve= 0 ,0
Exp/Cntr=0.3,0.1

Type RM Length L Ch R = 1 ,1042    ,417,417,417
BEGIN DESCRIPTION:
Little Stink Creek Trib1 4348
END DESCRIPTION:
XS GIS Cut Line= 3
      1431869.17      6863645.36      1432105.34      6863487.62
      1432557.96      6863216.33
#Sta/Elev= 30
    4716 1974.51  4831.3 1974.28  4940.9 1973.71  4955.9 1967.13  4970.9 1966.04
  4976.9 1963.55  5003.5 1961.83    5004 1961.33    5011 1961.83  5022.8 1965.36
  5028.6  1970.5  5034.6 1972.83  5044.2 1973.69    5050 1976.95  5139.4 1974.48
  5174.5 1968.38  5203.6 1968.98  5256.1 1966.07  5298.8 1970.06  5314.4 1972.56
  5320.2  1975.4  5357.2 1975.73    5363 1974.34  5378.5 1976.17  5384.4 1974.23
  5394.1 1975.26  5399.9 1973.85  5415.5 1976.41  5473.8 1979.16  5527.7 1979.87
#Mann= 4 ,-1 , 0
    4716     .16       0  4831.3     .07       0  5003.5     .07       0
    5011     .07       0
Bank Sta=5003.5,5011
XS Rating Curve= 0 ,0
Exp/Cntr=0.3,0.1

Type RM Length L Ch R = 1 ,625     ,263,263,263
BEGIN DESCRIPTION:
Little Stink Creek Trib1 4347
END DESCRIPTION:
XS GIS Cut Line= 3
      1432061.84      6863823.38      1432238.43      6863821.29
      1432731.52        6863579.
#Sta/Elev= 30
  4823.4 1972.25  4885.2 1972.53  4906.6 1972.93  4916.6 1971.29  4926.6 1964.44
  4936.6 1962.09  4946.6 1961.43  4976.6 1962.09  5015.8 1961.43  5021.4 1961.84
  5025.5 1960.58    5026 1960.08  5033.2 1960.08  5033.7 1960.58  5038.3 1964.36
  5043.9 1963.27  5051.9 1968.46  5060.8 1972.14  5074.2 1972.01  5111.3 1969.43
  5133.8 1969.73  5150.7 1972.51  5163.3 1972.94  5173.2 1972.56  5246.2 1973.25
  5319.3 1975.66  5419.6 1977.97  5448.5 1977.96  5486.4  1979.5  5549.4 1980.56
#Mann= 4 ,-1 , 0
  4823.4     .16       0  4885.2     .07       0  5025.5     .07       0
  5033.7     .07       0
Bank Sta=5025.5,5033.7
XS Rating Curve= 0 ,0
Exp/Cntr=0.3,0.1

Type RM Length L Ch R = 1 ,362     ,263,263,263
BEGIN DESCRIPTION:
Little Stink Creek Trib1 4346
END DESCRIPTION:
XS GIS Cut Line= 3
      1432111.44      6863978.06      1432305.36      6864058.15
      1432820.29      6864126.86
#Sta/Elev= 30
  4790.2  1971.6  4815.7 1970.96  4846.3 1971.44  4907.8 1971.68  4931.7 1969.16
  4945.5 1964.69    4961 1962.35    4978 1960.93  5015.7 1960.38  5016.2 1959.88
    5024 1960.38  5029.9 1961.49  5035.8 1964.76  5040.9  1964.9  5050.1 1971.09
  5060.2    1972  5070.3 1971.31  5090.4 1971.72  5186.6 1970.82  5187.7 1970.85
  5265.2 1971.32  5302.3 1972.39  5312.4  1973.4  5332.6 1973.26  5362.8 1974.94
    5383 1975.07  5393.1 1975.98  5423.4 1974.85  5494.2 1975.91  5519.5 1977.54
#Mann= 7 ,-1 , 0
  4790.2     .16       0  4846.3     .07       0  5015.7     .07       0
    5024     .07       0  5186.6    .035       0  5187.7     .07       0
  5494.2    .035       0
Bank Sta=5015.7,5024
XS Rating Curve= 0 ,0
Exp/Cntr=0.3,0.1

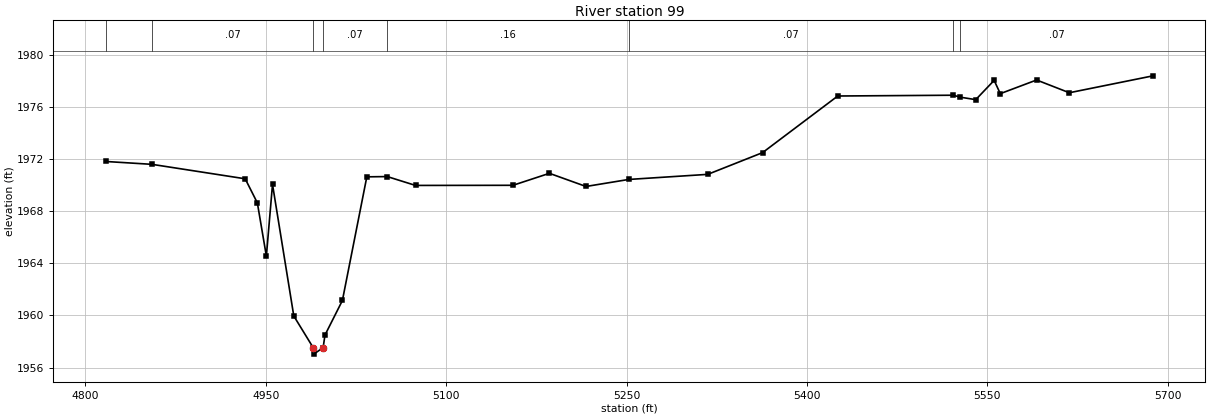
Type RM Length L Ch R = 1 ,99      ,0,0,0
BEGIN DESCRIPTION:
Little Stink Creek Trib1 4345
END DESCRIPTION:
XS GIS Cut Line= 3
      1432120.21      6864264.09      1432301.33      6864289.52
      1432980.64      6864182.46
#Sta/Elev= 30
  4817.1 1971.83  4855.5 1971.61    4933  1970.5  4943.1 1968.65  4950.6 1964.56
  4955.7 1970.07  4973.4 1959.96  4989.5 1957.53    4990 1957.03  4997.8 1957.53
  4999.3 1958.49  5013.8 1961.15  5034.1 1970.65  5051.1 1970.67  5074.6 1969.99
  5155.6    1970  5185.9 1970.92  5216.3 1969.91  5251.9 1970.45  5317.5 1970.84
  5363.1 1972.51  5425.6 1976.86  5521.7 1976.92  5527.4 1976.77  5540.3 1976.58
  5555.6 1978.06  5560.7 1977.04  5590.9 1978.09  5618.1 1977.11  5687.7 1978.41
#Mann= 8 ,-1 , 0
  4817.1     .16       0  4855.5     .07       0  4989.5     .07       0
  4997.8     .07       0  5051.1     .16       0  5251.9     .07       0
  5521.7    .035       0  5527.4     .07       0
Bank Sta=4989.5,4997.8
XS Rating Curve= 0 ,0
Exp/Cntr=0.3,0.1

Chan Stop Cuts=-1
Use User Specified Reach Order=0
Composite Channel Slope=5