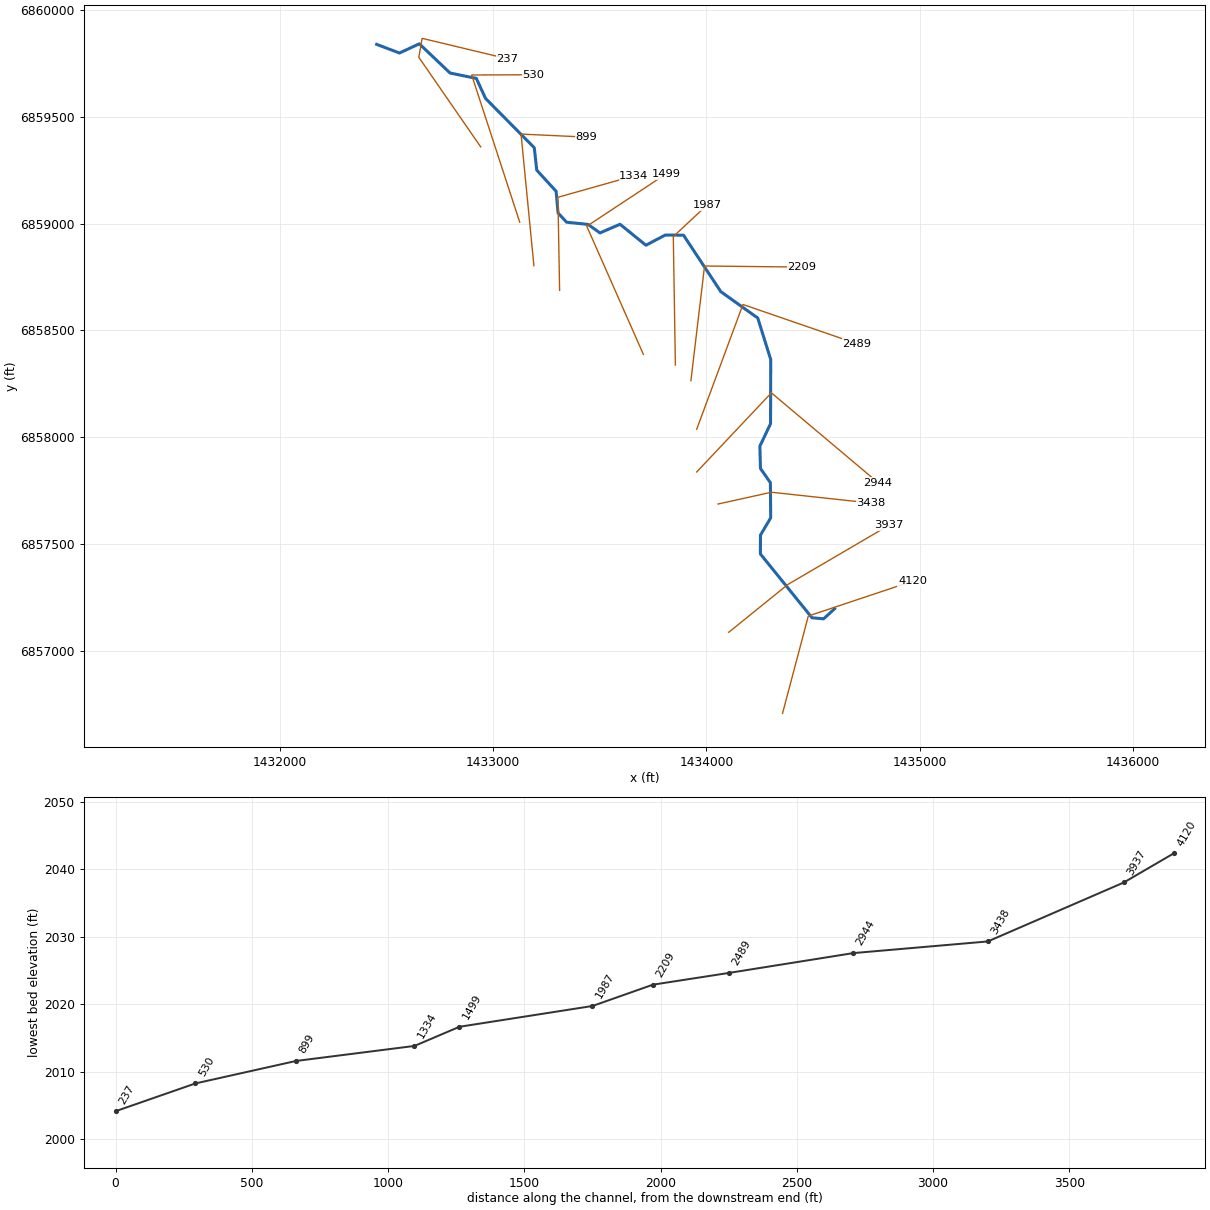
--- Little Stink Creek Trib1T1.prj (project) ---

Proj Title=Little Stink Creek Trib1T1 Base Level Engineering
Current Plan=p01
Default Exp/Contr=0.3,0.1
English Units
Geom File=g01
Flow File=f01
Plan File=p01
Y Axis Title=Elevation
X Axis Title(PF)=Main Channel Distance
X Axis Title(XS)=Station
BEGIN DESCRIPTION:
Little Stink Creek Trib1T1
END DESCRIPTION:
DSS Export Rating Curves= 0
DSS Export Rating Curve Sorted= 0
DSS Export Volume Flow Curves= 0
DXF OffsetX= 0
DXF OffsetY= 0
DXF ScaleX= 1
DXF ScaleY= 10

--- Little Stink Creek Trib1T1.p01 (plan) ---

Plan Title=Multiple Run
Short Identifier=Multiple
Geom File=g01
Flow File=f01
Subcritical Flow
K Sum by GR= 0
Std Step Tol= 0.01
Critical Tol= 0.01
Num of Std Step Trials= 20
Max Error Tol= 0.3
Flow Tol Ratio= 0.001
Split Flow NTrial= 30
Split Flow Tol= 0.02
Split Flow Ratio= 0.02
Log Output Level= 0
Friction Slope Method= 1
Unsteady Friction Slope Method= 2
Unsteady Bridges Friction Slope Method= 1
Parabolic Critical Depth
Global Vel Dist=  1 , 1 , 1
Global Log Level= 0
CheckData=True
Encroach Param= -1, 0, 0, 0
BEGIN DESCRIPTION:
Multiple Run
END DESCRIPTION:

--- Little Stink Creek Trib1T1.f01 (steady flow) ---

Flow Title=Multiple
Program Version=4.10
Number of Profiles= 7
Profile Names=10-year,25-year,50-year,1pct_min,100-year,1pct_plu,500-year
River Rch & RM=Little Stink Cre,Reach-1         ,4120
     295     422     530     331     661    1319    1043
Boundary for River Rch & Prof#=Little Stink Cre,Reach-1         , 1
Up Type= 0
Dn Type= 3
Dn Slope=0.014
Boundary for River Rch & Prof#=Little Stink Cre,Reach-1         , 2
Up Type= 0
Dn Type= 3
Dn Slope=0.014
Boundary for River Rch & Prof#=Little Stink Cre,Reach-1         , 3
Up Type= 0
Dn Type= 3
Dn Slope=0.014
Boundary for River Rch & Prof#=Little Stink Cre,Reach-1         , 4
Up Type= 0
Dn Type= 3
Dn Slope=0.014
Boundary for River Rch & Prof#=Little Stink Cre,Reach-1         , 5
Up Type= 0
Dn Type= 3
Dn Slope=0.014
Boundary for River Rch & Prof#=Little Stink Cre,Reach-1         , 6
Up Type= 0
Dn Type= 3
Dn Slope=0.014
Boundary for River Rch & Prof#=Little Stink Cre,Reach-1         , 7
Up Type= 0
Dn Type= 3
Dn Slope=0.014
DSS Import GetInterval= 0
DSS Import GetPeak= 0
DSS Import FillOption= 0

--- Little Stink Creek Trib1T1.g01 (geometry) ---

Geom Title=Existing Conditions

River Reach=Little Stink Cre,Reach-1
Reach XY= 30
      1434601.53      6857198.42      1434549.91      6857151.08
      1434495.42      6857155.88      1434253.49      6857454.31
      1434253.69      6857542.44      1434301.73      6857623.33
      1434300.31      6857787.91      1434253.78      6857854.36
      1434251.03      6857958.58      1434301.01      6858063.63
      1434301.96      6858363.59      1434241.02      6858558.22
      1434068.02      6858681.37      1433893.19      6858945.44
      1433807.58      6858946.26      1433716.87      6858898.38
      1433595.47      6858996.75      1433501.54      6858956.01
      1433445.63      6858995.86      1433345.03      6859006.14
      1433305.04      6859049.67      1433295.99      6859150.83
      1433205.15      6859249.92      1433193.66      6859354.59
      1432965.16      6859585.22      1432922.07      6859678.95
      1432799.10      6859703.94      1432654.95      6859840.62
      1432561.64      6859797.69      1432455.00      6859838.00

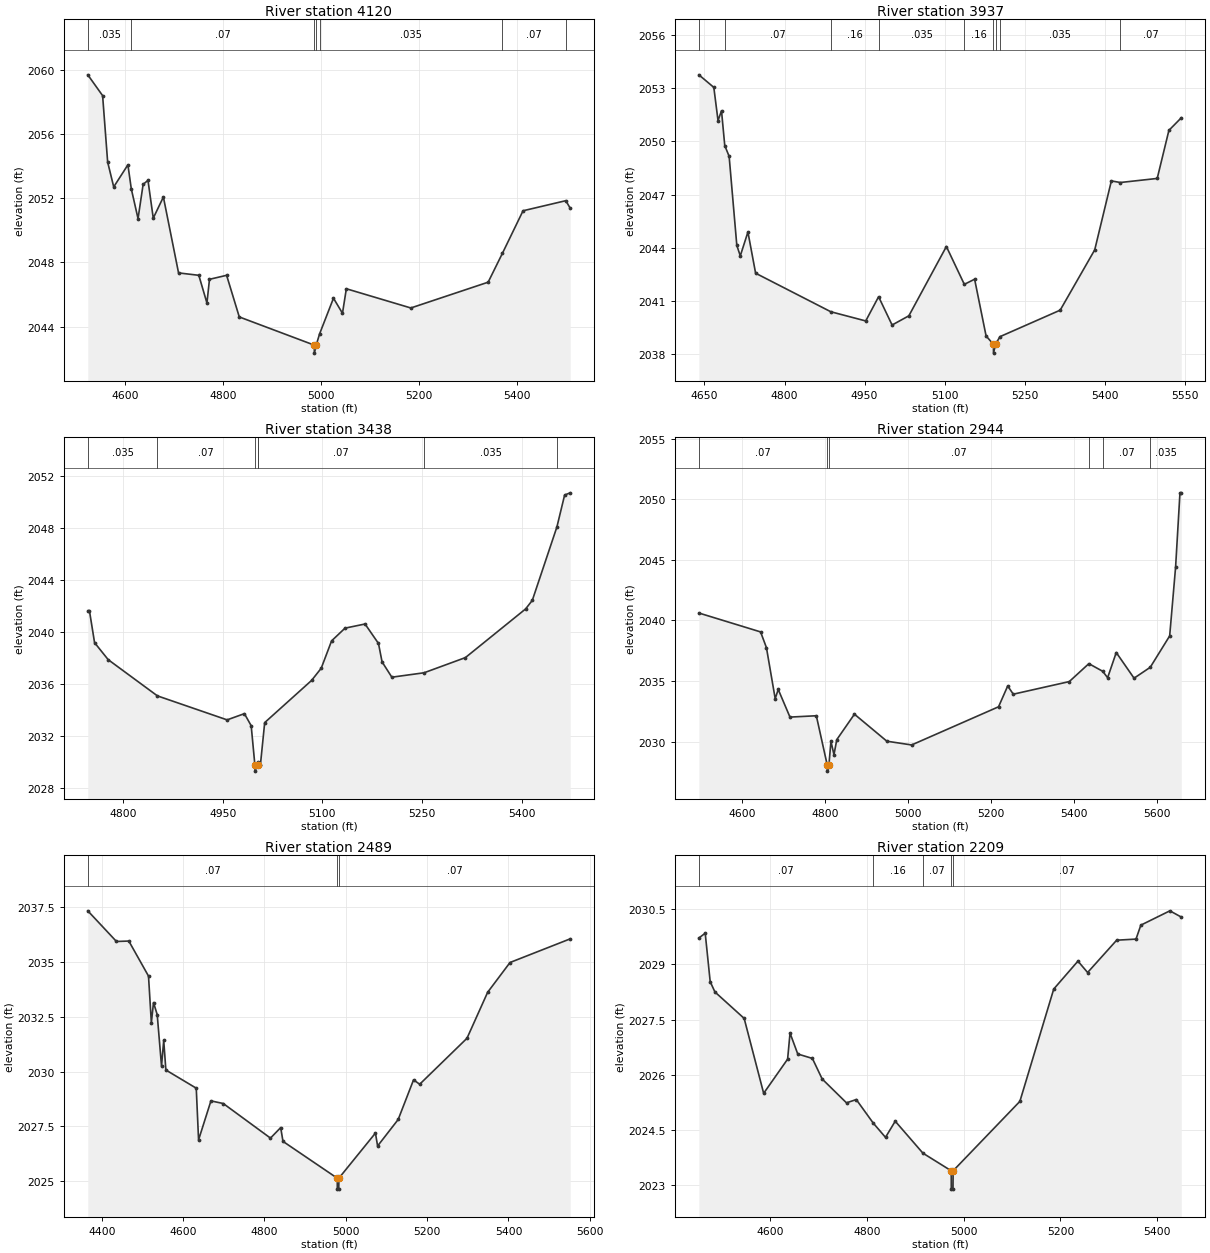
Type RM Length L Ch R = 1,4120,183,183,183
BEGIN DESCRIPTION:
Little Stink Creek Trib1T1 4202
END DESCRIPTION:
XS GIS Cut Line= 3
      1434357.20      6856708.72      1434478.11      6857164.04
      1434966.48      6857326.89
#Sta/Elev= 30
  4523.2 2059.72  4553.5 2058.42  4563.8 2054.27  4576.2 2052.72  4605.2 2054.10
  4612.1 2052.60  4625.9 2050.74  4636.3 2052.88  4646.2 2053.13  4657.0 2050.77
  4677.7 2052.09  4708.7 2047.35  4750.1 2047.20  4766.7 2045.47  4771.9 2046.95
  4806.9 2047.20  4832.8 2044.60  4986.0 2042.84  4986.3 2042.34  4990.0 2042.84
  4996.9 2043.54  5025.3 2045.77  5043.7 2044.83  5051.6 2046.36  5183.4 2045.16
  5341.4 2046.77  5370.5 2048.57  5412.7 2051.23  5500.1 2051.86  5509.1 2051.39
#Mann=7,-1,0
  4523.2   0.035       0  4612.1    0.07       0  4986.0   0.035       0
  4990.0    0.07       0  4996.9   0.035       0  5370.5    0.07       0
  5500.1    0.16       0
Bank Sta=4986,4990
Exp/Cntr=0.3,0.1

Type RM Length L Ch R = 1,3937,499,499,499
BEGIN DESCRIPTION:
Little Stink Creek Trib1T1 5.0
END DESCRIPTION:
XS GIS Cut Line= 3
      1434105.02      6857088.02      1434381.98      6857311.46
      1434855.02      6857588.01
#Sta/Elev= 30
  4639.5 2053.77  4667.5 2053.06  4675.4 2051.18  4681.9 2051.74  4688.0 2049.77
  4696.2 2049.16  4710.6 2044.12  4717.1 2043.53  4731.4 2044.88  4745.8 2042.55
  4886.7 2040.37  4952.1 2039.85  4976.2 2041.22  5001.5 2039.62  5032.9 2040.14
  5103.2 2044.06  5136.8 2041.92  5156.1 2042.21  5177.6 2039.00  5191.3 2038.53
  5191.5 2038.03  5195.3 2038.53  5203.5 2038.96  5316.4 2040.46  5381.1 2043.87
  5412.3 2047.77  5429.1 2047.68  5498.2 2047.91  5520.1 2050.63  5543.3 2051.34
#Mann=9,-1,0
  4639.5   0.035       0  4688.0    0.07       0  4886.7    0.16       0
  4976.2   0.035       0  5136.8    0.16       0  5191.3   0.035       0
  5195.3    0.16       0  5203.5   0.035       0  5429.1    0.07       0
Bank Sta=5191.3,5195.3
Exp/Cntr=0.3,0.1

Type RM Length L Ch R = 1,3438,494,494,494
BEGIN DESCRIPTION:
Little Stink Creek Trib1T1 4.0
END DESCRIPTION:
XS GIS Cut Line= 3
      1434055.02      6857688.00      1434305.45      6857743.18
      1434771.66      6857692.46
#Sta/Elev= 30
  4747.2 2041.65  4749.7 2041.65  4757.4 2039.19  4777.9 2037.88  4851.9 2035.09
  4956.7 2033.24  4982.7 2033.72  4992.9 2032.79  4998.4 2029.79  4998.7 2029.29
  5002.4 2029.79  5002.5 2029.82  5003.7 2029.98  5006.8 2029.79  5013.2 2033.03
  5083.7 2036.28  5098.2 2037.22  5113.8 2039.33  5134.0 2040.31  5164.1 2040.63
  5184.3 2039.13  5189.7 2037.71  5204.4 2036.53  5252.8 2036.87  5315.0 2038.04
  5405.5 2041.79  5415.6 2042.45  5452.6 2048.11  5464.2 2050.57  5472.6 2050.74
#Mann=8,-1,0
  4747.2   0.035       0  4851.9    0.07       0  4998.4    0.07       0
  5002.4    0.07       0  5002.5   0.035       0  5003.7    0.07       0
  5252.8   0.035       0  5452.6    0.16       0
Bank Sta=4998.4,5002.4
Exp/Cntr=0.3,0.1

Type RM Length L Ch R = 1,2944,455,455,455
BEGIN DESCRIPTION:
Little Stink Creek Trib1T1 3.0
END DESCRIPTION:
XS GIS Cut Line= 3
      1433954.99      6857837.99      1434305.00      6858208.00
      1434804.98      6857788.01
#Sta/Elev= 30
  4495.7 2040.61  4644.4 2039.05  4658.5 2037.75  4679.6 2033.54  4686.9 2034.30
  4715.2 2032.02  4778.7 2032.13  4805.0 2028.06  4805.3 2027.56  4809.0 2028.06
  4813.9 2030.02  4821.2 2028.92  4828.0 2030.16  4870.5 2032.26  4948.6 2030.03
  5008.3 2029.72  5217.7 2032.87  5239.8 2034.59  5253.2 2033.91  5388.1 2034.95
  5435.3 2036.43  5468.7 2035.80  5480.5 2035.27  5501.3 2037.35  5544.2 2035.23
  5583.2 2036.13  5630.0 2038.72  5644.3 2044.41  5654.8 2050.53  5658.0 2050.53
#Mann=6,-1,0
  4495.7    0.07       0  4805.0    0.07       0  4809.0    0.07       0
  5435.3   0.035       0  5468.7    0.07       0  5583.2   0.035       0
Bank Sta=4805,4809
Exp/Cntr=0.3,0.1

Type RM Length L Ch R = 1,2489,280,280,280
BEGIN DESCRIPTION:
Little Stink Creek Trib1T1 2.0
END DESCRIPTION:
XS GIS Cut Line= 3
      1433955.01      6858038.02      1434171.70      6858621.36
      1434704.97      6858438.01
#Sta/Elev= 30
  4365.6 2037.34  4436.1 2035.94  4466.5 2035.96  4514.9 2034.36  4521.9 2032.23
  4527.2 2033.15  4536.3 2032.60  4546.9 2030.25  4552.3 2031.42  4557.6 2030.07
  4632.3 2029.24  4638.0 2026.88  4668.4 2028.66  4698.7 2028.54  4814.8 2026.96
  4839.9 2027.44  4845.6 2026.81  4979.0 2025.13  4979.2 2024.63  4982.7 2024.63
  4983.0 2025.13  5072.9 2027.19  5078.2 2026.60  5128.8 2027.81  5166.6 2029.62
  5181.7 2029.42  5298.0 2031.52  5348.8 2033.62  5403.8 2034.98  5551.8 2036.06
#Mann=3,-1,0
  4365.6    0.07       0  4979.0    0.07       0  4983.0    0.07       0
Bank Sta=4979,4983
Exp/Cntr=0.3,0.1

Type RM Length L Ch R = 1,2209,222,222,222
BEGIN DESCRIPTION:
Little Stink Creek Trib1T1 4124
END DESCRIPTION:
XS GIS Cut Line= 3
      1433927.79      6858265.03      1433991.75      6858801.37
      1434448.59      6858796.30
#Sta/Elev= 30
  4452.7 2029.72  4465.8 2029.85  4476.1 2028.53  4485.9 2028.25  4546.3 2027.53
  4586.6 2025.49  4636.1 2026.42  4641.1 2027.13  4657.1 2026.56  4687.3 2026.44
  4707.5 2025.88  4757.8 2025.23  4778.0 2025.32  4813.0 2024.68  4838.4 2024.29
  4858.5 2024.73  4915.7 2023.86  4974.2 2023.38  4974.4 2022.88  4977.9 2022.88
  4978.2 2023.38  5116.1 2025.27  5186.1 2028.33  5236.1 2029.09  5256.1 2028.78
  5316.1 2029.66  5356.1 2029.69  5366.1 2030.07  5426.1 2030.46  5449.7 2030.29
#Mann=5,-1,0
  4452.7    0.07       0  4813.0    0.16       0  4915.7    0.07       0
  4974.2    0.07       0  4978.2    0.07       0
Bank Sta=4974.2,4978.2
Exp/Cntr=0.3,0.1

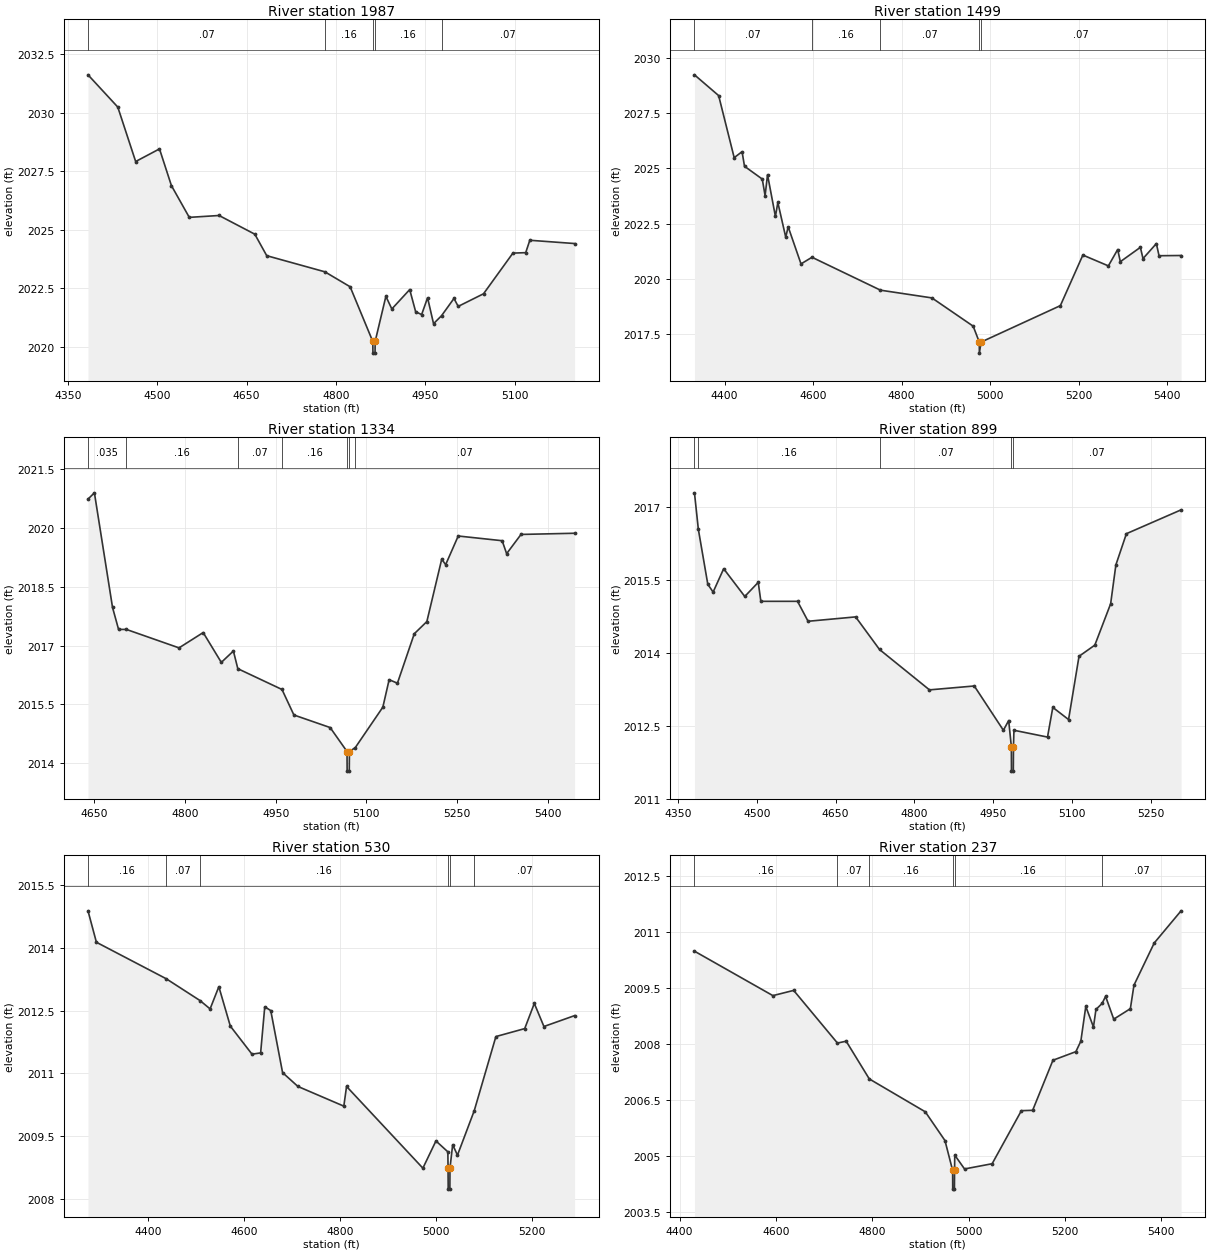
Type RM Length L Ch R = 1,1987,488,488,488
BEGIN DESCRIPTION:
Little Stink Creek Trib1T1 1.0
END DESCRIPTION:
XS GIS Cut Line= 3
      1433855.00      6858338.03      1433845.25      6858938.91
      1434003.04      6859086.18
#Sta/Elev= 30
  4383.7 2031.63  4433.7 2030.25  4463.7 2027.92  4503.7 2028.46  4523.7 2026.89
  4553.7 2025.53  4603.7 2025.61  4663.7 2024.81  4683.7 2023.89  4781.3 2023.20
  4823.7 2022.56  4861.7 2020.22  4862.0 2019.72  4865.5 2019.72  4865.7 2020.22
  4883.7 2022.15  4893.7 2021.61  4923.7 2022.44  4933.7 2021.49  4943.7 2021.37
  4953.7 2022.09  4963.7 2020.98  4977.1 2021.32  4998.0 2022.06  5005.1 2021.72
  5047.6 2022.26  5096.9 2024.00  5118.4 2024.02  5125.3 2024.55  5200.5 2024.41
#Mann=5,-1,0
  4383.7    0.07       0  4781.3    0.16       0  4861.7    0.07       0
  4865.7    0.16       0  4977.1    0.07       0
Bank Sta=4861.7,4865.7
Exp/Cntr=0.3,0.1

Type RM Length L Ch R = 1,1499,165,165,165
BEGIN DESCRIPTION:
Little Stink Creek Trib1T1 0.1
END DESCRIPTION:
XS GIS Cut Line= 3
      1433704.99      6858388.03      1433439.77      6858987.20
      1433810.23      6859231.32
#Sta/Elev= 30
  4332.1 2029.24  4386.7 2028.30  4421.8 2025.49  4439.6 2025.76  4445.1 2025.10
  4485.2 2024.52  4491.6 2023.77  4497.1 2024.72  4514.9 2022.83  4520.4 2023.46
  4538.2 2021.89  4543.7 2022.36  4572.7 2020.68  4597.5 2020.98  4752.2 2019.49
  4868.3 2019.14  4961.5 2017.86  4975.3 2017.14  4975.5 2016.64  4979.3 2017.14
  5158.4 2018.79  5209.2 2021.08  5266.8 2020.59  5287.8 2021.33  5293.8 2020.78
  5339.1 2021.43  5345.0 2020.92  5375.2 2021.60  5381.2 2021.05  5431.0 2021.06
#Mann=5,-1,0
  4332.1    0.07       0  4597.5    0.16       0  4752.2    0.07       0
  4975.3    0.07       0  4979.3    0.07       0
Bank Sta=4975.3,4979.3
Exp/Cntr=0.3,0.1

Type RM Length L Ch R = 1,1334,435,435,435
BEGIN DESCRIPTION:
Little Stink Creek Trib1T1 4125
END DESCRIPTION:
XS GIS Cut Line= 3
      1433312.37      6858687.40      1433304.47      6859122.77
      1433660.41      6859222.89
#Sta/Elev= 30
  4639.3 2020.73  4649.9 2020.89  4679.9 2017.97  4689.9 2017.41  4702.8 2017.41
  4789.9 2016.94  4829.9 2017.33  4859.9 2016.57  4879.9 2016.86  4887.2 2016.41
  4960.3 2015.88  4980.0 2015.23  5040.0 2014.91  5067.9 2014.30  5068.1 2013.80
  5071.6 2013.80  5071.9 2014.30  5081.6 2014.40  5127.2 2015.43  5137.6 2016.13
  5151.3 2016.04  5179.2 2017.30  5200.0 2017.61  5224.6 2019.20  5231.1 2019.06
  5251.9 2019.79  5324.6 2019.67  5332.0 2019.34  5355.8 2019.83  5444.5 2019.86
#Mann=7,-1,0
  4639.3   0.035       0  4702.8    0.16       0  4887.2    0.07       0
  4960.3    0.16       0  5067.9    0.07       0  5071.9    0.16       0
  5081.6    0.07       0
Bank Sta=5067.9,5071.9
Exp/Cntr=0.3,0.1

Type RM Length L Ch R = 1,899,369,369,369
BEGIN DESCRIPTION:
Little Stink Creek Trib1T1 4267
END DESCRIPTION:
XS GIS Cut Line= 3
      1433191.87      6858802.69      1433131.61      6859418.45
      1433438.98      6859404.27
#Sta/Elev= 30
  4381.3 2017.29  4388.7 2016.54  4406.7 2015.41  4416.8 2015.25  4436.9 2015.73
  4477.1 2015.16  4502.7 2015.45  4507.7 2015.06  4577.5 2015.06  4597.6 2014.65
  4688.1 2014.74  4733.6 2014.07  4828.7 2013.24  4914.0 2013.32  4969.4 2012.41
  4979.5 2012.61  4984.6 2012.07  4984.8 2011.57  4988.3 2011.57  4988.6 2012.07
  4989.5 2012.41  5053.4 2012.27  5063.5 2012.88  5093.5 2012.63  5113.4 2013.93
  5143.5 2014.16  5173.6 2015.01  5183.6 2015.81  5203.6 2016.45  5307.7 2016.94
#Mann=5,-1,0
  4381.3   0.035       0  4388.7    0.16       0  4733.6    0.07       0
  4984.6    0.07       0  4988.6    0.07       0
Bank Sta=4984.6,4988.6
Exp/Cntr=0.3,0.1

Type RM Length L Ch R = 1,530,293,293,293
BEGIN DESCRIPTION:
Little Stink Creek Trib1T1 4268
END DESCRIPTION:
XS GIS Cut Line= 3
      1433125.44      6859006.38      1432900.24      6859694.89
      1433188.94      6859695.94
#Sta/Elev= 30
  4275.6 2014.88  4293.1 2014.13  4438.4 2013.26  4508.7 2012.74  4529.8 2012.54
  4548.0 2013.07  4571.9 2012.13  4617.0 2011.46  4635.0 2011.49  4643.6 2012.59
  4656.1 2012.50  4680.7 2011.02  4712.6 2010.69  4808.2 2010.22  4813.9 2010.69
  4972.8 2008.74  5000.0 2009.39  5024.8 2009.13  5025.2 2008.74  5025.5 2008.24
  5029.0 2008.24  5029.2 2008.74  5034.8 2009.30  5044.8 2009.05  5079.7 2010.11
  5124.8 2011.88  5184.8 2012.07  5204.8 2012.67  5224.8 2012.12  5288.7 2012.38
#Mann=6,-1,0
  4275.6    0.16       0  4438.4    0.07       0  4508.7    0.16       0
  5025.2    0.07       0  5029.2    0.16       0  5079.7    0.07       0
Bank Sta=5025.2,5029.2
Exp/Cntr=0.3,0.1

Type RM Length L Ch R = 1,237,0,0,0
BEGIN DESCRIPTION:
Little Stink Creek Trib1T1 4473
END DESCRIPTION:
XS GIS Cut Line= 4
      1432942.37      6859358.70      1432652.40      6859777.76
      1432668.03      6859866.30      1433067.37      6859770.81
#Sta/Elev= 30
  4430.8 2010.49  4593.6 2009.30  4636.7 2009.44  4727.6 2008.03  4745.7 2008.08
  4793.7 2007.07  4909.9 2006.19  4950.8 2005.42  4966.7 2004.62  4966.9 2004.12
  4970.4 2004.12  4970.7 2004.62  4971.1 2005.03  4991.4 2004.66  5048.7 2004.80
  5109.4 2006.22  5132.8 2006.23  5174.9 2007.57  5222.5 2007.80  5232.8 2008.08
  5243.1 2009.01  5259.0 2008.46  5264.2 2008.93  5276.9 2009.09  5284.2 2009.28
  5301.1 2008.67  5335.6 2008.95  5343.1 2009.58  5385.2 2010.71  5440.9 2011.57
#Mann=6,-1,0
  4430.8    0.16       0  4727.6    0.07       0  4793.7    0.16       0
  4966.7    0.07       0  4970.7    0.16       0  5276.9    0.07       0
Bank Sta=4966.7,4970.7
Exp/Cntr=0.3,0.1

Chan Stop Cuts=-1