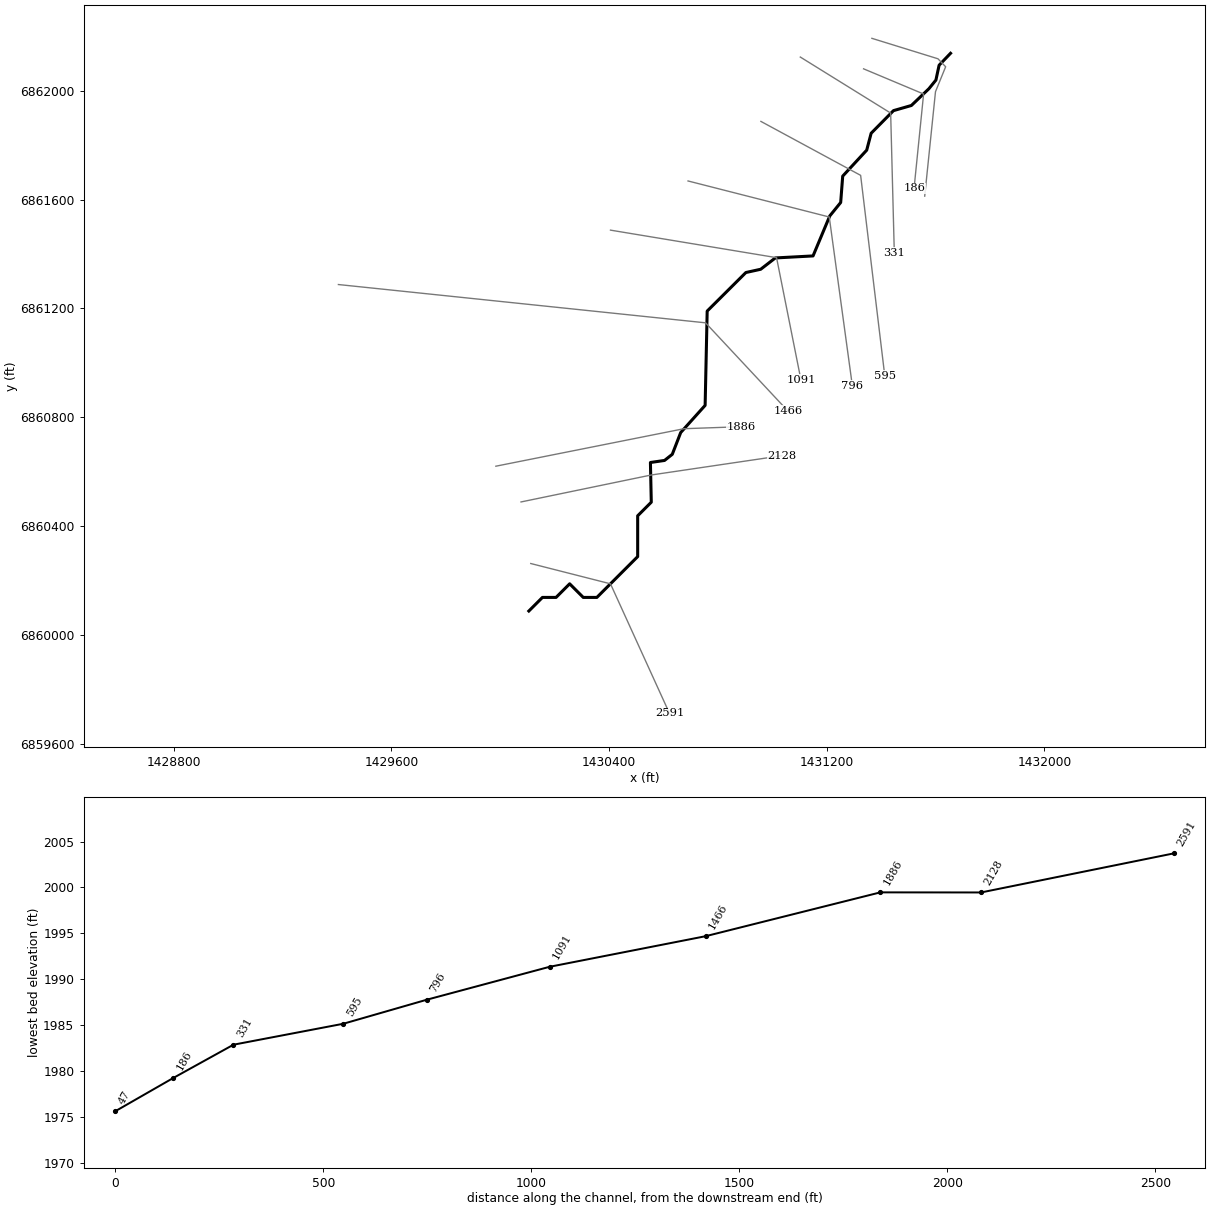
--- Little Stink Creek Trib1T2.prj (project) ---

Proj Title=Little Stink Creek Trib1T2 Base Level Engineering
Current Plan=p01
Default Exp/Contr=0.3,0.1
English Units
Geom File=g01
Flow File=f01
Plan File=p01
Y Axis Title=Elevation
X Axis Title(PF)=Main Channel Distance
X Axis Title(XS)=Station
BEGIN DESCRIPTION:
Little Stink Creek Trib1T2
END DESCRIPTION:
DSS Export Rating Curves= 0
DSS Export Rating Curve Sorted= 0
DSS Export Volume Flow Curves= 0
DXF OffsetX= 0
DXF OffsetY= 0
DXF ScaleX= 1
DXF ScaleY= 10

--- Little Stink Creek Trib1T2.p01 (plan) ---

Plan Title=Multiple Run
Short Identifier=Multiple
Geom File=g01
Flow File=f01
Subcritical Flow
K Sum by GR= 0
Std Step Tol= 0.01
Critical Tol= 0.01
Num of Std Step Trials= 20
Max Error Tol= 0.3
Flow Tol Ratio= 0.001
Split Flow NTrial= 30
Split Flow Tol= 0.02
Split Flow Ratio= 0.02
Log Output Level= 0
Friction Slope Method= 1
Unsteady Friction Slope Method= 2
Unsteady Bridges Friction Slope Method= 1
Parabolic Critical Depth
Global Vel Dist=  1 , 1 , 1
Global Log Level= 0
CheckData=True
Encroach Param= -1, 0, 0, 0
BEGIN DESCRIPTION:
Multiple Run
END DESCRIPTION:

--- Little Stink Creek Trib1T2.f01 (steady flow) ---

Flow Title=Multiple
Program Version=4.10
Number of Profiles= 7
Profile Names=10-year,25-year,50-year,1pct_min,100-year,1pct_plu,500-year
River Rch & RM=Little Stink Cre,Reach-1         ,2591
     254     358     447     277     553    1104     859
Boundary for River Rch & Prof#=Little Stink Cre,Reach-1         , 1
Up Type= 0
Dn Type= 3
Dn Slope=0.026
Boundary for River Rch & Prof#=Little Stink Cre,Reach-1         , 2
Up Type= 0
Dn Type= 3
Dn Slope=0.026
Boundary for River Rch & Prof#=Little Stink Cre,Reach-1         , 3
Up Type= 0
Dn Type= 3
Dn Slope=0.026
Boundary for River Rch & Prof#=Little Stink Cre,Reach-1         , 4
Up Type= 0
Dn Type= 3
Dn Slope=0.026
Boundary for River Rch & Prof#=Little Stink Cre,Reach-1         , 5
Up Type= 0
Dn Type= 3
Dn Slope=0.026
Boundary for River Rch & Prof#=Little Stink Cre,Reach-1         , 6
Up Type= 0
Dn Type= 3
Dn Slope=0.026
Boundary for River Rch & Prof#=Little Stink Cre,Reach-1         , 7
Up Type= 0
Dn Type= 3
Dn Slope=0.026
DSS Import GetInterval= 0
DSS Import GetPeak= 0
DSS Import FillOption= 0

--- Little Stink Creek Trib1T2.g01 (geometry) ---

Geom Title=Existing Conditions
Program Version=4.10

River Reach=Little Stink Cre,Reach-1
Reach XY= 30
        1430105.        6860088.        1430155.        6860138.
        1430205.        6860138.        1430255.        6860188.
        1430305.        6860138.        1430355.        6860138.
        1430505.        6860288.        1430505.        6860438.
        1430555.        6860488.      1430551.86      6860633.91
      1430603.75      6860641.45      1430632.19      6860664.03
      1430663.19      6860744.02      1430752.94      6860843.86
      1430760.46      6861190.45       1430902.7      6861332.17
      1430957.17      6861344.14      1431010.94      6861385.75
      1431149.59      6861393.18      1431211.12      6861540.18
      1431251.17      6861589.59      1431258.62       6861686.5
      1431346.82      6861781.96      1431363.15      6861844.07
       1431445.3      6861927.23      1431511.06      6861946.15
      1431575.42      6862007.76       1431601.2      6862039.57
      1431612.94      6862094.14        1431655.        6862138.

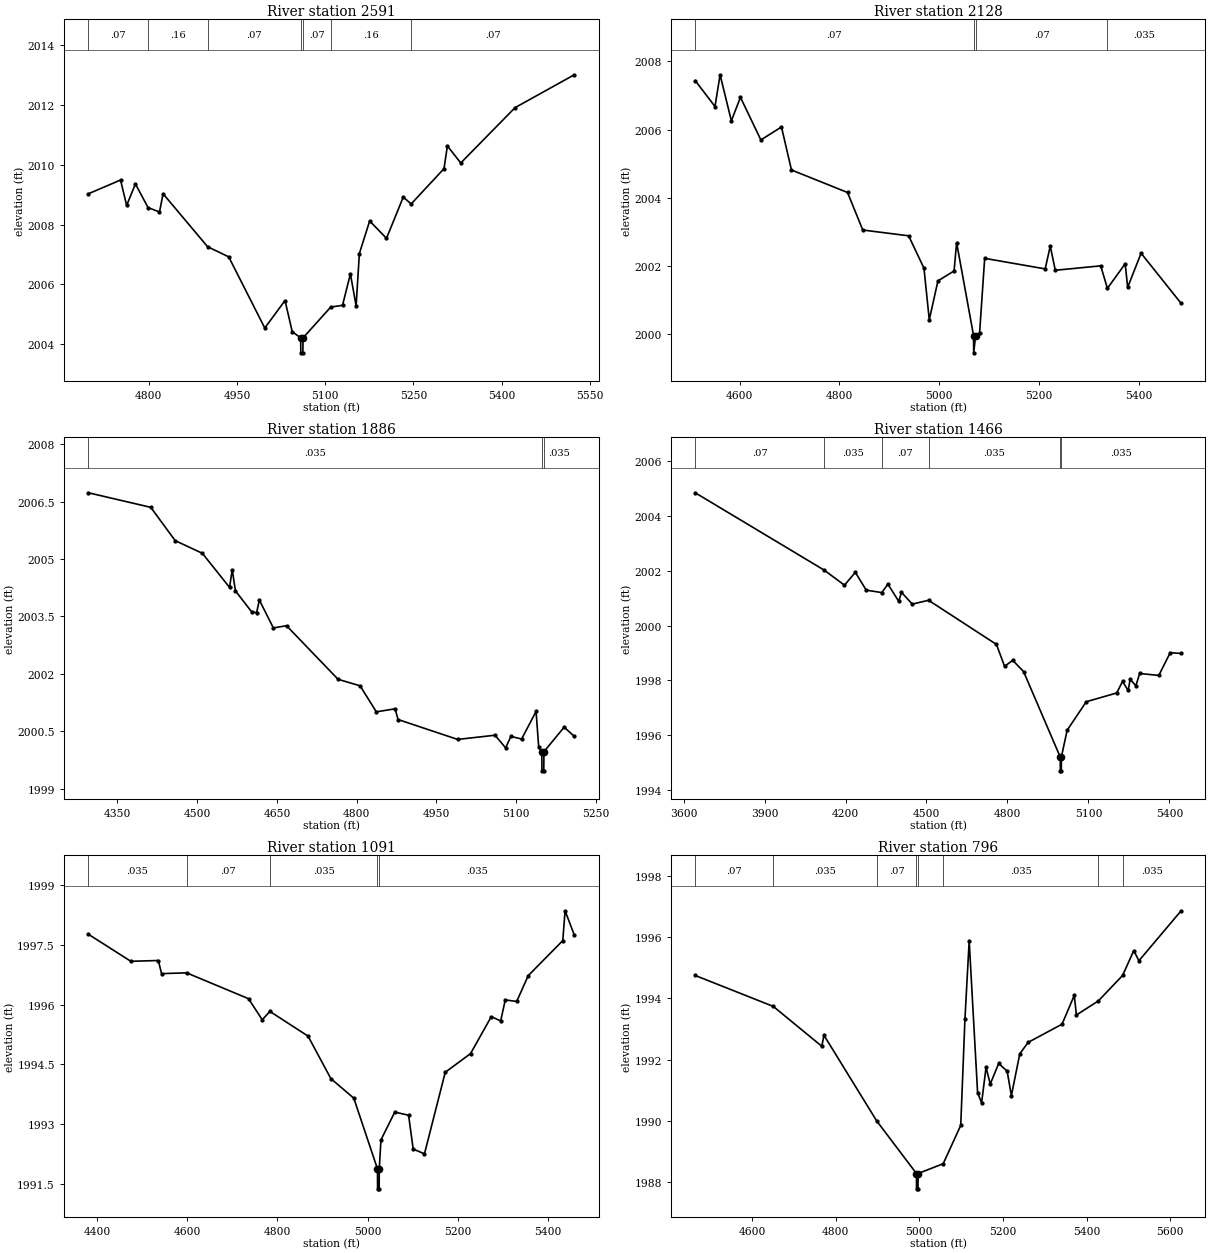
Type RM Length L Ch R = 1 ,2591    ,463,463,463
BEGIN DESCRIPTION:
Little Stink Creek Trib1T2 4204
END DESCRIPTION:
XS GIS Cut Line= 3
      1430112.04      6860262.58        1430405.        6860188.
      1430621.92      6859711.78
#Sta/Elev= 30
  4697.7 2009.03  4752.3 2009.49  4762.7 2008.64  4777.6 2009.36    4799 2008.57
  4818.5 2008.42  4824.6 2009.03  4900.2 2007.26  4936.1 2006.92  4997.4 2004.54
  5031.8 2005.46    5044 2004.42  5058.4 2004.21  5058.6 2003.71  5062.1 2003.71
  5062.4 2004.21  5109.4 2005.24  5129.5  2005.3  5142.9 2006.35  5152.6 2005.28
  5158.1 2007.03  5175.6 2008.12  5204.2 2007.54  5232.7 2008.92  5246.1 2008.69
  5301.9 2009.87  5307.7 2010.63  5330.4 2010.06  5422.6 2011.91  5523.3 2013.01
#Mann= 7 ,-1 , 0
  4697.7     .07       0    4799     .16       0  4900.2     .07       0
  5058.4     .07       0  5062.4     .07       0  5109.4     .16       0
  5246.1     .07       0
Bank Sta=5058.4,5062.4
XS Rating Curve= 0 ,0
Exp/Cntr=0.3,0.1

Type RM Length L Ch R = 1 ,2128    ,242,242,242
BEGIN DESCRIPTION:
Little Stink Creek Trib1T2 3.0
END DESCRIPTION:
XS GIS Cut Line= 3
      1430076.25       6860488.9        1430555.        6860588.
      1431034.39       6860658.9
#Sta/Elev= 30
  4511.1 2007.44  4550.7 2006.68  4560.9 2007.61  4583.5 2006.26  4601.7 2006.95
  4642.6  2005.7  4683.9 2006.08  4703.9 2004.82  4816.2 2004.16  4846.8 2003.06
  4938.7 2002.89  4969.4 2001.94    4980 2000.43  4997.4 2001.57  5029.7 2001.86
  5034.8 2002.69  5068.8 1999.96    5069 1999.46  5072.8 1999.96  5080.9 2000.05
    5091 2002.23  5212.3 2001.92  5222.4 2002.59  5232.5 2001.88  5323.5 2002.01
  5336.9 2001.35  5372.5 2002.07  5377.5 2001.38  5404.4 2002.38  5484.6 2000.91
#Mann= 4 ,-1 , 0
  4511.1     .07       0  5068.8     .07       0  5072.8     .07       0
  5336.9    .035       0
Bank Sta=5068.8,5072.8
XS Rating Curve= 0 ,0
Exp/Cntr=0.3,0.1

Type RM Length L Ch R = 1 ,1886    ,420,420,420
BEGIN DESCRIPTION:
Little Stink Creek Trib1T2 2.0
END DESCRIPTION:
XS GIS Cut Line= 3
      1429983.74       6860620.3      1430674.84      6860758.06
      1430884.11      6860765.46
#Sta/Elev= 30
  4295.3 2006.73  4412.6 2006.35  4458.6 2005.48  4509.7 2005.15  4560.8 2004.26
  4565.9 2004.72  4571.9 2004.17  4602.5 2003.62  4611.8  2003.6  4616.9 2003.93
  4643.3  2003.2    4668 2003.26    4765 2001.86  4806.4 2001.69    4837 2001.01
  4872.3 2001.09  4877.8 2000.81    4990 2000.29  5060.2  2000.4  5080.2 2000.07
  5090.2 2000.37  5110.2  2000.3  5137.5 2001.02  5142.5 2000.08  5148.3 1999.97
  5148.5 1999.47    5152 1999.47  5152.3 1999.97  5190.3 2000.61  5209.4 2000.37
#Mann= 3 ,-1 , 0
  4295.3    .035       0  5148.3    .035       0  5152.3    .035       0
Bank Sta=5148.3,5152.3
XS Rating Curve= 0 ,0
Exp/Cntr=0.3,0.1

Type RM Length L Ch R = 1 ,1466    ,375,375,375
BEGIN DESCRIPTION:
Little Stink Creek Trib1T2 1.0
END DESCRIPTION:
XS GIS Cut Line= 3
      1429405.02        6861288.       1430754.5       6861147.3
      1431057.12      6860823.22
#Sta/Elev= 30
  3643.2 2004.84  4120.9 2002.02  4196.2 2001.47  4236.4 2001.94  4276.6 2001.29
  4334.4  2001.2    4357 2001.51  4397.2 2000.88  4407.3 2001.21  4447.5 2000.78
  4507.6 2000.92  4759.2 1999.31  4789.4 1998.51  4819.5 1998.73  4859.7 1998.32
  4995.7  1995.2    4996  1994.7  4999.5  1994.7  4999.7  1995.2  5021.1 1996.18
    5092 1997.22  5204.8 1997.54  5226.3 1997.96  5247.3 1997.63  5254.6 1998.04
  5275.7  1997.8  5289.8 1998.25  5360.7 1998.18  5403.2 1999.01  5443.4 1998.98
#Mann= 6 ,-1 , 0
  3643.2     .07       0  4120.9    .035       0  4334.4     .07       0
  4507.6    .035       0  4995.7    .035       0  4999.7    .035       0
Bank Sta=4995.7,4999.7
XS Rating Curve= 0 ,0
Exp/Cntr=0.3,0.1

Type RM Length L Ch R = 1 ,1091    ,295,295,295
BEGIN DESCRIPTION:
Little Stink Creek Trib1T2 0.1
END DESCRIPTION:
XS GIS Cut Line= 3
      1430405.05      6861487.99      1431015.51      6861386.78
        1431105.      6860938.02
#Sta/Elev= 30
  4381.2 1997.77  4475.2 1997.09  4536.1 1997.11  4543.3 1996.78  4598.7  1996.8
  4735.9 1996.15  4766.3 1995.62  4783.3 1995.83  4867.7 1995.21  4918.4 1994.14
  4969.1 1993.65  5021.6 1991.87  5021.8 1991.37  5025.3 1991.37  5025.6 1991.87
  5029.3  1992.6  5059.9  1993.3  5090.5 1993.22  5100.7 1992.37  5125.7 1992.25
  5171.7  1994.3  5227.8 1994.77  5273.8  1995.7  5294.5 1995.59  5304.7 1996.12
    5330 1996.08  5355.6 1996.73  5432.1 1997.61  5437.2 1998.36  5457.6 1997.75
#Mann= 5 ,-1 , 0
  4381.2    .035       0  4598.7     .07       0  4783.3    .035       0
  5021.6    .035       0  5025.6    .035       0
Bank Sta=5021.6,5025.6
XS Rating Curve= 0 ,0
Exp/Cntr=0.3,0.1

Type RM Length L Ch R = 1 ,796     ,201,201,201
BEGIN DESCRIPTION:
Little Stink Creek Trib1T2 4064
END DESCRIPTION:
XS GIS Cut Line= 3
      1430690.12      6861668.69      1431209.19      6861536.26
      1431294.07      6860915.84
#Sta/Elev= 30
  4464.3 1994.75    4651 1993.74    4767 1992.44  4772.1  1992.8    4898 1990.01
  4993.3 1988.29  4993.5 1987.79    4997 1987.79  4997.3 1988.29  5057.3 1988.61
  5099.2 1989.86  5109.3 1993.34  5119.4 1995.88  5139.5 1990.93  5149.1 1990.59
  5159.7 1991.75  5169.8 1991.21    5190 1991.88  5210.2 1991.63  5220.3 1990.83
  5240.5  1992.2  5260.7 1992.57  5341.4 1993.16  5370.7  1994.1  5375.8 1993.46
  5428.3 1993.92  5486.2 1994.75    5513 1995.56  5525.3 1995.23  5626.2 1996.86
#Mann= 8 ,-1 , 0
  4464.3     .07       0    4651    .035       0    4898     .07       0
  4993.3     .07       0  4997.3     .07       0  5057.3    .035       0
  5428.3     .07       0  5486.2    .035       0
Bank Sta=4993.3,4997.3
XS Rating Curve= 0 ,0
Exp/Cntr=0.3,0.1

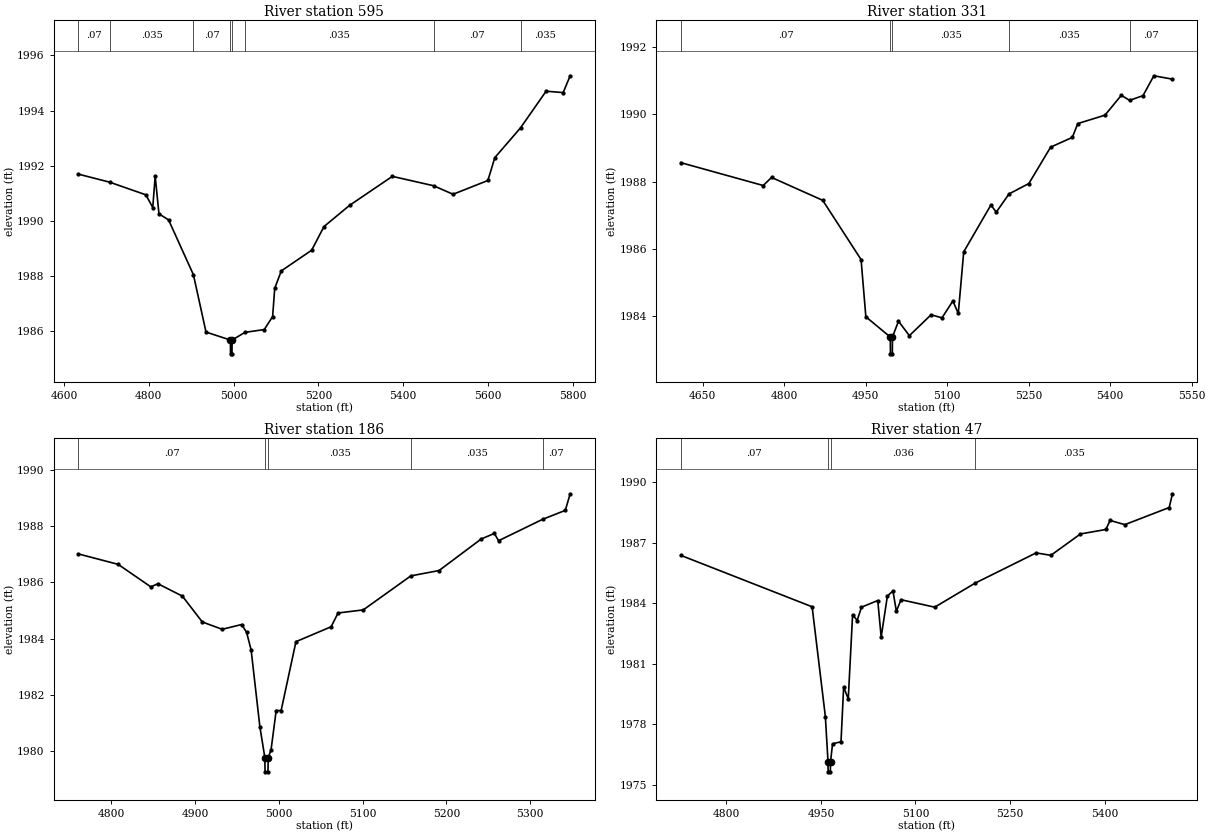
Type RM Length L Ch R = 1 ,595     ,264,264,264
BEGIN DESCRIPTION:
Little Stink Creek Trib1T2 4065
END DESCRIPTION:
XS GIS Cut Line= 3
      1430957.97       6861887.6      1431324.51      6861689.33
      1431413.36      6860951.59
#Sta/Elev= 30
    4634 1991.69  4707.5  1991.4  4793.1 1990.94  4809.3 1990.48    4815 1991.62
  4823.9 1990.25  4846.6 1990.03  4905.2 1988.04  4934.9 1985.96  4992.4 1985.67
  4992.7 1985.17  4996.2 1985.17  4996.4 1985.67  5026.7 1985.95  5072.2 1986.05
    5092 1986.52    5097 1987.55  5112.5 1988.18  5184.1 1988.93  5213.2 1989.79
  5273.7 1990.56  5374.4 1991.61  5471.7 1991.27  5517.6 1990.96  5599.7 1991.46
  5616.1 1992.29  5676.7 1993.37    5737  1994.7  5777.3 1994.65  5793.8 1995.26
#Mann= 8 ,-1 , 0
    4634     .07       0  4707.5    .035       0  4905.2     .07       0
  4992.4     .07       0  4996.4     .07       0  5026.7    .035       0
  5471.7     .07       0  5676.7    .035       0
Bank Sta=4992.4,4996.4
XS Rating Curve= 0 ,0
Exp/Cntr=0.3,0.1

Type RM Length L Ch R = 1 ,331     ,145,145,145
BEGIN DESCRIPTION:
Little Stink Creek Trib1T2 4066
END DESCRIPTION:
XS GIS Cut Line= 3
      1431102.75      6862124.18      1431434.87      6861918.23
      1431448.29       6861403.8
#Sta/Elev= 30
  4609.2 1988.57  4761.1 1987.89  4776.5 1988.13  4870.7 1987.45  4941.3 1985.69
  4950.1 1983.99  4995.1 1983.39  4995.4 1982.89  4998.9 1982.89  4999.1 1983.39
  5010.2 1983.86  5030.2 1983.43  5070.2 1984.05  5090.3 1983.96  5110.3 1984.46
  5120.3 1984.09  5130.3 1985.92  5180.3 1987.31  5190.3  1987.1  5213.7 1987.64
  5250.3 1987.95  5290.3 1989.03  5330.3 1989.32  5340.3 1989.73  5390.4 1989.98
  5420.4 1990.57  5435.7 1990.42  5460.4 1990.56  5480.4 1991.15  5514.6 1991.05
#Mann= 5 ,-1 , 0
  4609.2     .07       0  4995.1    .035       0  4999.1    .035       0
  5213.7    .035       0  5435.7     .07       0
Bank Sta=4995.1,4999.1
XS Rating Curve= 0 ,0
Exp/Cntr=0.3,0.1

Type RM Length L Ch R = 1 ,186     ,139,139,139
BEGIN DESCRIPTION:
Little Stink Creek Trib1T2 4475
END DESCRIPTION:
XS GIS Cut Line= 3
       1431335.3       6862080.9      1431555.96       6861988.3
      1431520.96      6861642.27
#Sta/Elev= 30
  4760.7 1987.01  4808.1 1986.64  4847.1 1985.84  4855.6 1985.95  4884.8 1985.51
  4908.6 1984.59  4932.3 1984.33  4955.6  1984.5  4961.5 1984.22  4966.9 1983.59
  4977.3 1980.87  4983.3 1979.76  4983.5 1979.26    4987 1979.26  4987.3 1979.76
  4990.7 1980.05  4996.8 1981.44  5002.7 1981.44  5020.4 1983.89  5062.4 1984.42
  5070.7 1984.91  5100.8 1985.02  5157.6 1986.23  5191.3 1986.42  5241.5 1987.54
  5257.3 1987.74  5262.3 1987.48  5314.8 1988.24    5342 1988.56  5347.8 1989.15
#Mann= 5 ,-1 , 0
  4760.7     .07       0  4983.3    .035       0  4987.3    .035       0
  5157.6    .035       0  5314.8     .07       0
Bank Sta=4983.3,4987.3
XS Rating Curve= 0 ,0
Exp/Cntr=0.3,0.1

Type RM Length L Ch R = 1 ,47      ,0,0,0
BEGIN DESCRIPTION:
Little Stink Creek Trib1T2 4067
END DESCRIPTION:
XS GIS Cut Line= 5
       1431365.9      6862192.95      1431608.77      6862117.79
      1431636.98      6862088.49      1431599.66      6861996.86
      1431560.01      6861612.95
#Sta/Elev= 30
  4727.7 1986.38  4936.1 1983.83  4957.1 1978.39  4961.3 1976.15  4961.5 1975.65
    4965 1975.65  4965.3 1976.15  4968.5 1977.04  4981.9 1977.14  4986.1 1979.86
  4993.4 1979.26  5000.3 1983.44  5007.5 1983.15  5014.4 1983.81  5040.2 1984.14
  5045.6 1982.33  5055.5 1984.37  5064.3 1984.61  5069.7 1983.61  5077.1 1984.18
  5130.5 1983.81  5194.5    1985  5291.3  1986.5  5314.7 1986.38  5361.7 1987.44
  5401.9 1987.66  5408.6 1988.11    5432  1987.9  5502.4 1988.75  5507.5 1989.43
#Mann= 4 ,-1 , 0
  4727.7     .07       0  4961.3    .036       0  4965.3    .036       0
  5194.5    .035       0
Bank Sta=4961.3,4965.3
XS Rating Curve= 0 ,0
Exp/Cntr=0.3,0.1

Chan Stop Cuts=-1
Use User Specified Reach Order=0
Composite Channel Slope=5