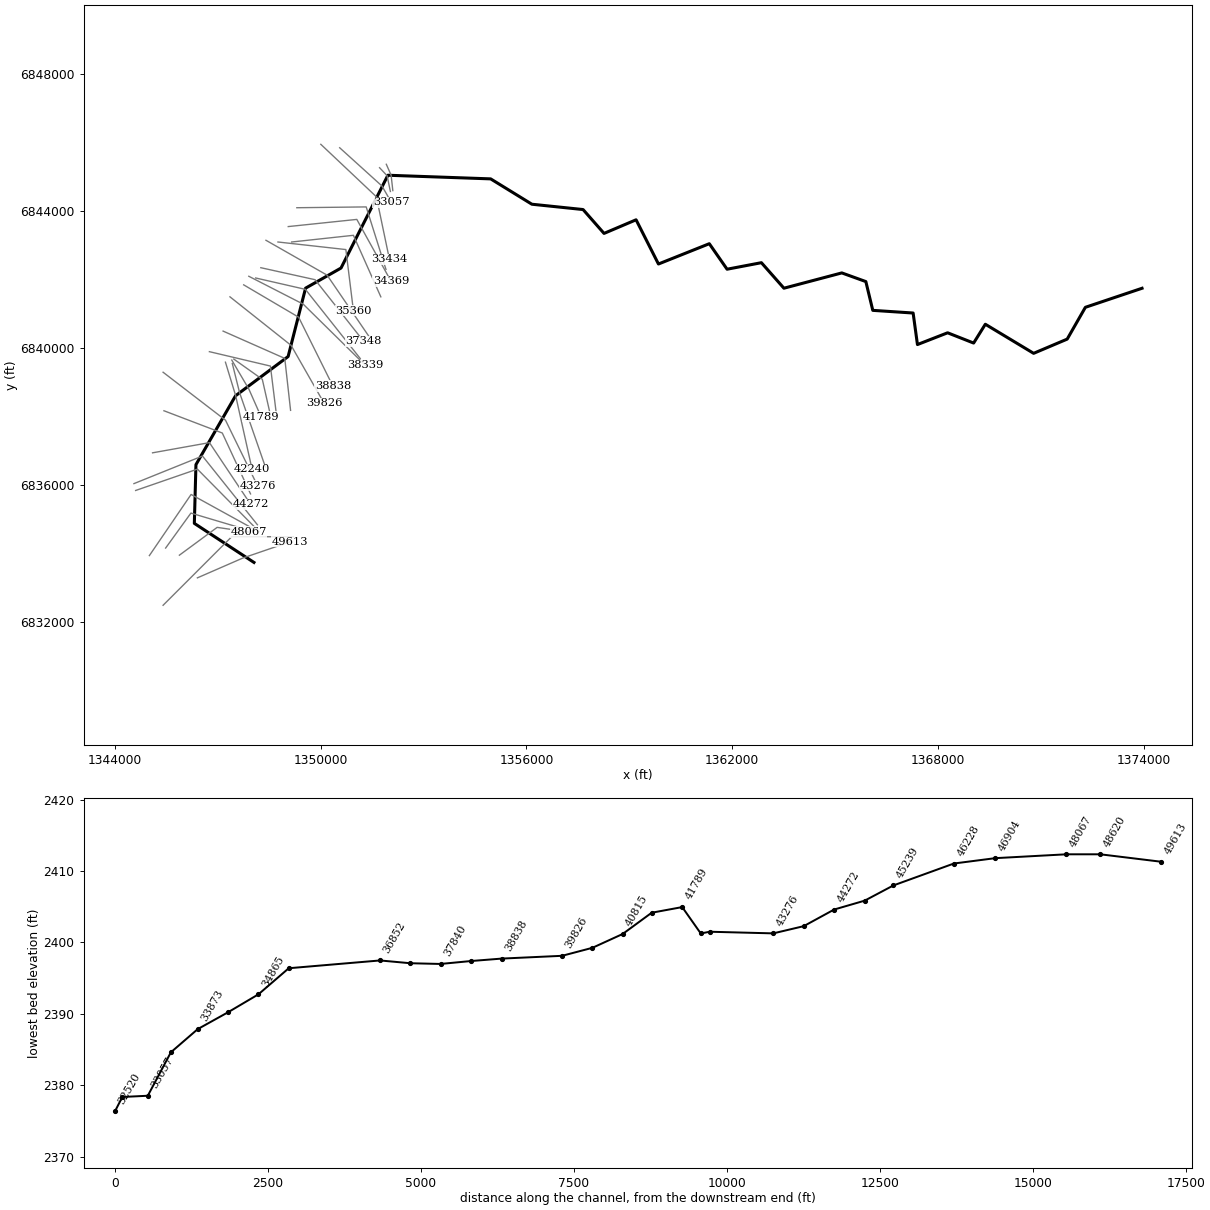
--- Long Branch.prj (project) ---

Proj Title=Long Branch Base Level Engineering
Current Plan=p01
Default Exp/Contr=0.3,0.1
English Units
Geom File=g01
Flow File=f01
Plan File=p01
Y Axis Title=Elevation
X Axis Title(PF)=Main Channel Distance
X Axis Title(XS)=Station
BEGIN DESCRIPTION:
Long Branch
END DESCRIPTION:
DSS Export Rating Curves= 0
DSS Export Rating Curve Sorted= 0
DSS Export Volume Flow Curves= 0
DXF OffsetX= 0
DXF OffsetY= 0
DXF ScaleX= 1
DXF ScaleY= 10

--- Long Branch.p01 (plan) ---

Plan Title=Multiple Run
Short Identifier=Multiple
Geom File=g01
Flow File=f01
Subcritical Flow
K Sum by GR= 0
Std Step Tol= 0.01
Critical Tol= 0.01
Num of Std Step Trials= 20
Max Error Tol= 0.3
Flow Tol Ratio= 0.001
Split Flow NTrial= 30
Split Flow Tol= 0.02
Split Flow Ratio= 0.02
Log Output Level= 0
Friction Slope Method= 1
Unsteady Friction Slope Method= 2
Unsteady Bridges Friction Slope Method= 1
Parabolic Critical Depth
Global Vel Dist=  1 , 1 , 1
Global Log Level= 0
CheckData=True
Encroach Param= -1, 0, 0, 0
BEGIN DESCRIPTION:
Multiple Run
END DESCRIPTION:

--- Long Branch.f01 (steady flow) ---

Flow Title=Multiple
Number of Profiles=7
Profile Names=10-year,25-year,50-year,1pct_min,100-year,1pct_plu,500-year
River Rch & RM= Long Branch,Reach-1,49613
     135     180     215     128     255     508     362
River Rch & RM= Long Branch,Reach-1,48620
     197     267     321     192     383     765     553
River Rch & RM= Long Branch,Reach-1,38838
     244     332     401     240     480     957     696
River Rch & RM= Long Branch,Reach-1,31944
     375     531     660     407     811    1619    1244
River Rch & RM= Long Branch,Reach-1,27224
     419     598     747     463     924    1844    1433
River Rch & RM= Long Branch,Reach-1,25267
     616     900    1145     720    1437    2868    2302
River Rch & RM= Long Branch,Reach-1,23815
     724    1069    1368     868    1731    3454    2813
River Rch & RM= Long Branch,Reach-1,21866
     767    1138    1461     929    1854    3700    3031
River Rch & RM= Long Branch,Reach-1,19878
     792    1178    1515     965    1926    3843    3159
River Rch & RM= Long Branch,Reach-1,18476
     829    1236    1592    1016    2028    4046    3337
River Rch & RM= Long Branch,Reach-1,17422
     844    1259    1623    1036    2067    4124    3404
River Rch & RM= Long Branch,Reach-1,15504
     891    1333    1723    1103    2200    4390    3641
River Rch & RM= Long Branch,Reach-1,10595
     903    1353    1750    1121    2236    4461    3704
River Rch & RM= Long Branch,Reach-1,8128
    1014    1517    1961    1255    2504    4996    4139
River Rch & RM= Long Branch,Reach-1,178
    1373    2080    2711    1748    3487    6957    5852
Boundary for River Rch & Prof#=Long Branch,Reach-1,1
Up Type=0
Dn Type=3
Dn Slope=0.005
Boundary for River Rch & Prof#=Long Branch,Reach-1,2
Up Type=0
Dn Type=3
Dn Slope=0.005
Boundary for River Rch & Prof#=Long Branch,Reach-1,3
Up Type=0
Dn Type=3
Dn Slope=0.005
Boundary for River Rch & Prof#=Long Branch,Reach-1,4
Up Type=0
Dn Type=3
Dn Slope=0.005
Boundary for River Rch & Prof#=Long Branch,Reach-1,5
Up Type=0
Dn Type=3
Dn Slope=0.005
Boundary for River Rch & Prof#=Long Branch,Reach-1,6
Up Type=0
Dn Type=3
Dn Slope=0.005
Boundary for River Rch & Prof#=Long Branch,Reach-1,7
Up Type=0
Dn Type=3
Dn Slope=0.005

--- Long Branch.g01 (geometry) ---

Geom Title=Existing Conditions
Program Version=4.10

River Reach=Long Branch     ,Reach-1
Reach XY= 30
        1348055.        6833738.      1346316.24      6834877.95
      1346363.04      6836591.32      1347518.33      6838601.33
      1349051.34      6839746.17      1349560.47      6841740.99
      1350594.05        6842328.      1351960.86      6845035.94
       1354958.3      6844929.92      1356160.45      6844190.18
      1357653.35       6844034.9      1358264.62      6843338.63
      1359199.22      6843735.92      1359851.57      6842445.79
      1361334.71      6843038.39       1361852.7      6842293.83
      1362854.01      6842484.47      1363510.85      6841739.49
      1365199.29      6842186.11        1365900.        6841933.
      1366102.53      6841093.45      1367278.99       6841015.7
      1367404.99      6840095.53      1368284.51      6840438.87
      1369043.41      6840139.38      1369384.64      6840688.39
      1370793.13      6839839.51      1371772.13      6840254.45
      1372302.45      6841182.27        1373955.        6841738.

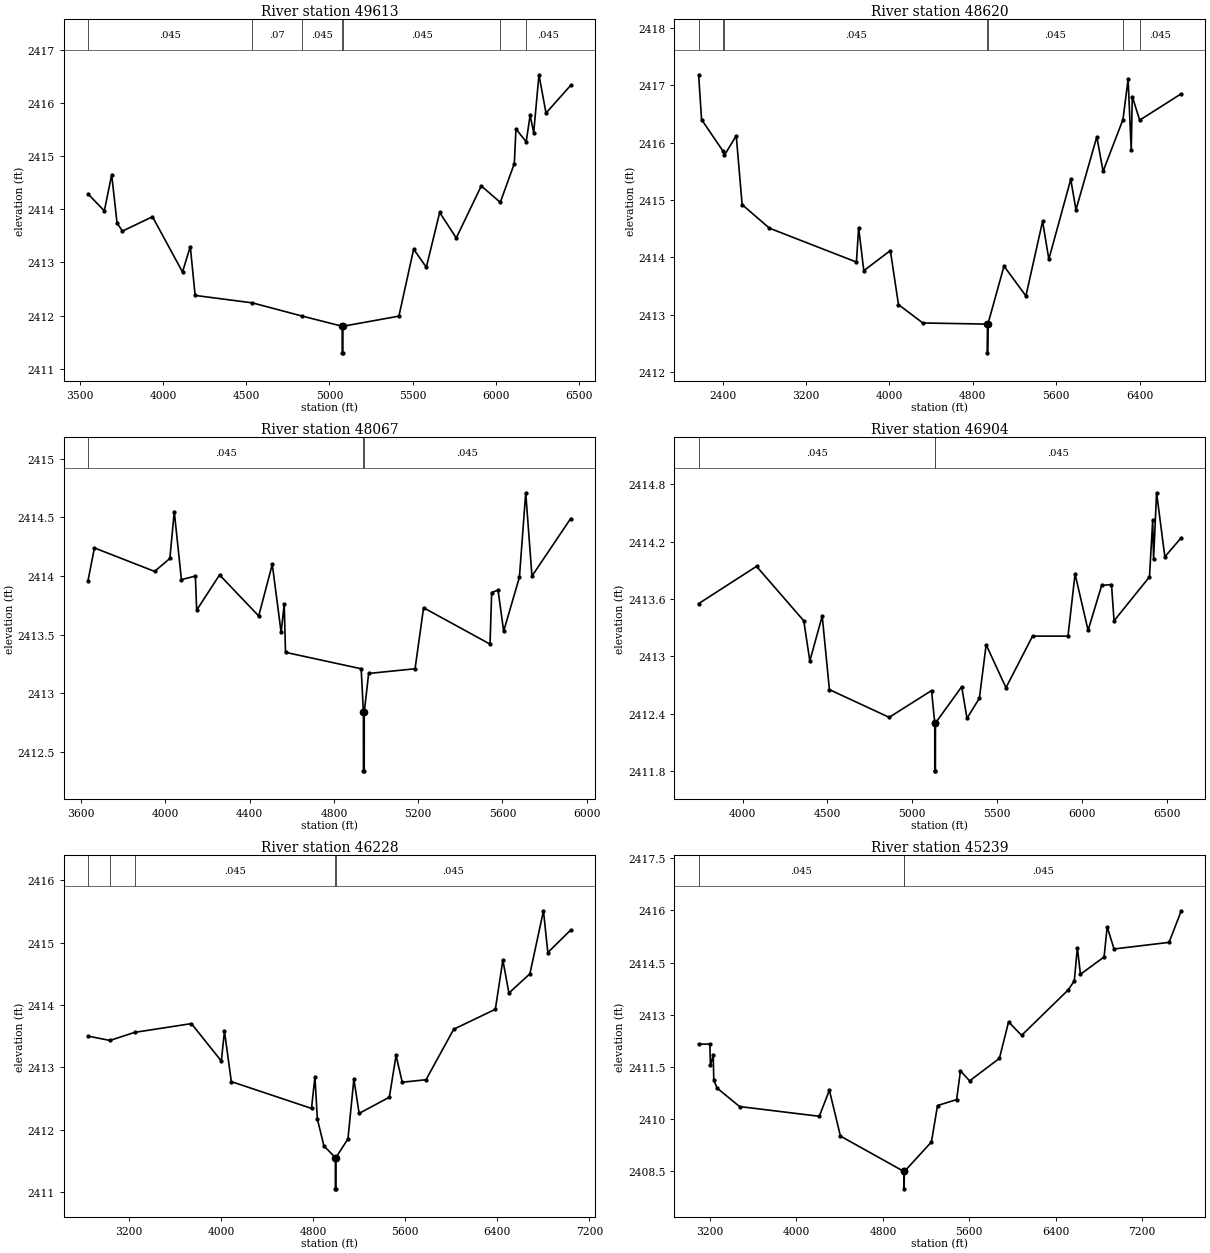
Type RM Length L Ch R = 1 ,49613   ,993,993,993
BEGIN DESCRIPTION:
Long Branch 88.0
END DESCRIPTION:
XS GIS Cut Line= 3
      1346404.99      6833287.99      1347734.81        6833868.
      1349105.04      6834338.01
#Sta/Elev= 30
  3549.2 2414.29  3647.4 2413.97  3691.6 2414.65  3723.8 2413.74  3756.4 2413.59
  3936.7 2413.86    4117 2412.82  4163.8  2413.3  4192.9 2412.38  4536.3 2412.24
  4837.6 2411.99  5076.3  2411.8  5076.5  2411.3    5080  2411.3  5080.3  2411.8
  5416.9 2411.99  5505.5 2413.25  5581.7 2412.91  5661.8 2413.94  5761.4 2413.46
  5911.9 2414.44  6025.9 2414.13  6110.3 2414.86  6120.2 2415.51  6181.6 2415.27
  6205.4 2415.77  6226.6 2415.44  6258.3 2416.53  6300.6 2415.81  6448.6 2416.33
#Mann= 7 ,-1 , 0
  3549.2    .045       0  4536.3     .07       0  4837.6    .045       0
  5076.3    .045       0  5080.3    .045       0  6025.9    .035       0
  6181.6    .045       0
Bank Sta=5076.3,5080.3
XS Rating Curve= 0 ,0
Exp/Cntr=0.3,0.1

Type RM Length L Ch R = 1 ,48620   ,553,553,553
BEGIN DESCRIPTION:
Long Branch 87.0
END DESCRIPTION:
XS GIS Cut Line= 3
        1345405.        6832488.      1347405.57      6834488.25
      1349204.97        6834488.
#Sta/Elev= 30
    2171 2417.18  2199.3  2416.4  2401.6 2415.86  2418.9 2415.78  2531.6 2416.12
  2588.2 2414.92  2849.8 2414.51  3684.2 2413.92  3705.4 2414.52  3754.9 2413.77
  4009.5 2414.12  4087.3 2413.18  4320.6 2412.86  4940.9 2412.84  4941.1 2412.34
  4944.9 2412.84  5099.4 2413.85  5309.4 2413.33  5469.4 2414.63  5529.4 2413.97
  5739.4 2415.36  5789.4 2414.83  5989.4  2416.1  6049.4  2415.5    6240  2416.4
  6289.4  2417.1  6319.4 2415.87  6329.4  2416.8  6400.5 2416.39  6799.4 2416.85
#Mann= 7 ,-1 , 0
    2171    .045       0  2401.6     .07       0  2418.9    .045       0
  4940.9    .045       0  4944.9    .045       0    6240    .035       0
  6400.5    .045       0
Bank Sta=4940.9,4944.9
XS Rating Curve= 0 ,0
Exp/Cntr=0.3,0.1

Type RM Length L Ch R = 1 ,48067   ,1163,1163,1163
BEGIN DESCRIPTION:
Long Branch 4284
END DESCRIPTION:
XS GIS Cut Line= 3
      1345880.33      6833949.81      1346981.73      6834761.36
      1347895.99      6834626.89
#Sta/Elev= 30
  3631.9 2413.96  3662.5 2414.24  3948.2 2414.04  4020.8 2414.15  4041.6 2414.55
  4075.6 2413.97  4141.9    2414  4148.1 2413.71  4256.8 2414.01  4442.7 2413.66
  4507.2  2414.1  4549.1 2413.52  4563.8 2413.76    4570 2413.35  4929.3 2413.21
  4939.9 2412.84  4940.2 2412.34  4943.8 2412.34    4944 2412.84  4964.8 2413.17
  5185.2 2413.21  5225.7 2413.73  5541.3 2413.42  5549.1 2413.86  5579.4 2413.88
    5606 2413.53  5680.8 2413.99  5710.8 2414.71  5740.4    2414  5924.1 2414.49
#Mann= 3 ,-1 , 0
  3631.9    .045       0  4939.9    .045       0    4944    .045       0
Bank Sta=4939.9,4944
XS Rating Curve= 0 ,0
Exp/Cntr=0.3,0.1

Type RM Length L Ch R = 1 ,46904   ,676,676,676
BEGIN DESCRIPTION:
Long Branch 4283
END DESCRIPTION:
XS GIS Cut Line= 3
       1345479.3      6834158.15       1346216.4      6835178.08
      1347734.48      6834725.86
#Sta/Elev= 30
  3741.6 2413.55  4082.5 2413.94  4360.9 2413.37  4396.5 2412.95  4469.4 2413.42
  4511.8 2412.65  4863.8 2412.36  5113.3 2412.64  5132.1  2412.3  5132.4  2411.8
    5136  2411.8  5136.3  2412.3  5290.7 2412.68    5322 2412.35    5395 2412.56
  5434.8 2413.12  5551.6 2412.67  5708.1 2413.21  5916.8 2413.21  5958.4 2413.86
  6035.2 2413.27    6115 2413.74    6173 2413.75    6188 2413.37  6396.7 2413.83
  6415.6 2414.42  6420.9 2414.02  6438.5 2414.71  6487.2 2414.04    6584 2414.24
#Mann= 3 ,-1 , 0
  3741.6    .045       0  5132.1    .045       0  5136.3    .045       0
Bank Sta=5132.1,5136.3
XS Rating Curve= 0 ,0
Exp/Cntr=0.3,0.1

Type RM Length L Ch R = 1 ,46228   ,989,989,989
BEGIN DESCRIPTION:
Long Branch 86.0
END DESCRIPTION:
XS GIS Cut Line= 3
      1345005.01      6833938.01      1346221.59      6835721.48
      1348004.99      6834738.01
#Sta/Elev= 30
  2841.1  2413.5  3031.8 2413.43  3247.5 2413.56  3740.1  2413.7  4000.3  2413.1
  4027.4 2413.58    4087 2412.77  4784.1 2412.34  4813.9 2412.85  4834.9 2412.17
  4891.8 2411.74  4991.4 2411.55  4991.7 2411.05  4995.3 2411.05  4995.6 2411.55
  5100.7 2411.85  5152.4 2412.81    5198 2412.26  5460.7 2412.52    5519 2413.19
  5572.9 2412.76  5779.3  2412.8  6020.3 2413.61  6382.1 2413.93  6447.5 2414.72
  6499.9 2414.19  6682.6  2414.5  6800.5 2415.51  6838.3 2414.84  7036.6  2415.2
#Mann= 5 ,-1 , 0
  2841.1    .045       0  3031.8     .07       0  3247.5    .045       0
  4991.4    .045       0  4995.6    .045       0
Bank Sta=4991.4,4995.6
XS Rating Curve= 0 ,0
Exp/Cntr=0.3,0.1

Type RM Length L Ch R = 1 ,45239   ,469,469,469
BEGIN DESCRIPTION:
Long Branch 85.0
END DESCRIPTION:
XS GIS Cut Line= 3
      1344604.96      6835837.99      1346405.41       6836460.7
        1348205.        6834638.
#Sta/Elev= 30
  3094.9 2412.15  3198.7 2412.15    3204 2411.54  3229.9 2411.83  3235.2 2411.11
  3266.4 2410.88    3474 2410.35  4211.4 2410.07  4304.9 2410.82    4407  2409.5
    4995 2408.48  4995.3 2407.98  4999.2 2408.48  5249.1 2409.33  5305.7 2410.38
  5482.4 2410.55  5517.8 2411.38  5602.7 2411.09  5878.4 2411.74  5963.3 2412.79
  6083.5  2412.4  6514.9 2413.71  6571.4 2413.97  6599.7 2414.93    6628 2414.16
  6847.2 2414.66  6875.5 2415.53  6939.2 2414.89  7448.3 2415.08  7561.4 2415.99
#Mann= 3 ,-1 , 0
  3094.9    .045       0    4995    .045       0  4999.2    .045       0
Bank Sta=4995,4999.2
XS Rating Curve= 0 ,0
Exp/Cntr=0.3,0.1

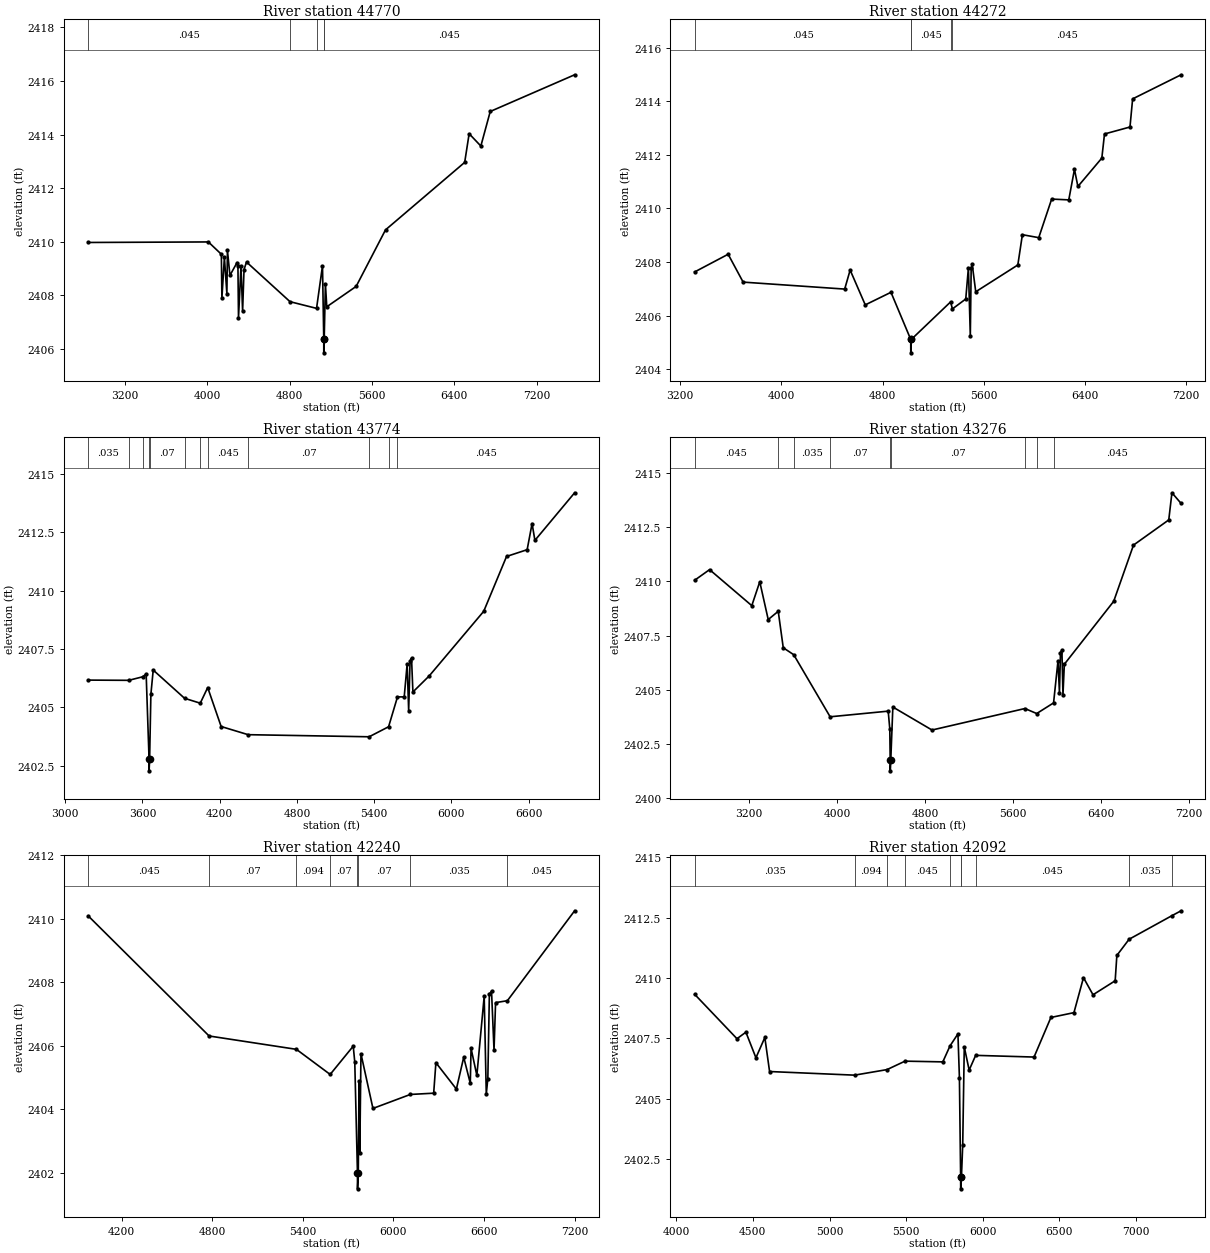
Type RM Length L Ch R = 1 ,44770   ,498,498,498
BEGIN DESCRIPTION:
Long Branch 84.0
END DESCRIPTION:
XS GIS Cut Line= 3
      1344554.97      6836037.99      1346552.85      6836843.89
        1348155.        6834838.
#Sta/Elev= 30
  2845.7 2409.97  4012.1 2409.99  4138.3 2409.53  4143.6 2407.89  4167.8 2409.42
  4191.9 2408.06  4197.3 2409.68  4221.5 2408.74  4290.6 2409.22  4299.3 2409.08
  4304.7 2407.15  4328.9 2409.09  4344.6  2407.4  4358.4 2408.96  4382.5 2409.24
  4804.8 2407.76  5062.3 2407.51    5120  2409.1  5132.3 2406.35  5132.5 2405.85
  5136.5 2406.35  5148.3 2408.42  5161.6 2407.57  5446.6 2408.33  5731.6 2410.44
  6500.1 2412.96  6543.3 2414.03    6657 2413.57  6748.2 2414.86  7567.2 2416.23
#Mann= 5 ,-1 , 0
  2845.7    .045       0  4804.8    .035       0  5062.3    .045       0
  5132.3    .035       0  5136.5    .045       0
Bank Sta=5132.3,5136.5
XS Rating Curve= 0 ,0
Exp/Cntr=0.3,0.1

Type RM Length L Ch R = 1 ,44272   ,498,498,498
BEGIN DESCRIPTION:
Long Branch 83.0
END DESCRIPTION:
XS GIS Cut Line= 3
       1345097.8      6836936.58      1346756.65      6837234.02
      1347954.99      6835438.01
#Sta/Elev= 30
  3314.7 2407.63  3579.4 2408.29  3697.9 2407.25  4500.5 2406.99  4543.6  2407.7
  4663.1  2406.4  4866.3 2406.87  5022.5 2405.11  5022.8 2404.61  5026.8 2405.11
  5337.3 2406.51    5352 2406.25  5457.3 2406.62  5478.3 2407.79  5493.3 2405.24
  5500.1 2407.77  5508.3 2407.91  5536.2 2406.89  5868.8 2407.89  5904.9 2409.02
  6034.1 2408.91  6136.2 2410.35  6271.4 2410.32  6316.4 2411.46  6343.5 2410.82
  6532.7 2411.88  6553.8 2412.78  6755.1 2413.04  6776.1 2414.09  7159.1 2414.99
#Mann= 5 ,-1 , 0
  3314.7    .045       0  5022.5    .045       0  5026.8    .045       0
  5337.3    .035       0    5352    .045       0
Bank Sta=5022.5,5026.8
XS Rating Curve= 0 ,0
Exp/Cntr=0.3,0.1

Type RM Length L Ch R = 1 ,43774   ,498,498,498
BEGIN DESCRIPTION:
Long Branch 82.0
END DESCRIPTION:
XS GIS Cut Line= 3
      1345429.86      6838163.97      1347131.78      6837514.32
        1347955.        6835738.
#Sta/Elev= 30
  3178.3 2406.17  3493.4 2406.16  3600.6 2406.31  3628.8 2406.43  3651.4 2402.78
  3651.7 2402.28  3655.7 2402.78  3665.5 2405.56  3683.6  2406.6  3927.1 2405.39
  4049.1 2405.18  4106.9 2405.85  4211.4 2404.18  4421.1 2403.83  5361.3 2403.74
  5512.3 2404.17  5581.5 2405.45  5633.8 2405.45  5656.7 2406.87  5668.3 2404.86
  5679.3    2407  5690.6 2407.11  5701.3 2405.66  5828.1 2406.35  6251.6 2409.12
  6428.8 2411.47  6588.9 2411.76  6627.2 2412.88  6649.2 2412.16  6957.8  2414.2
#Mann= 12 ,-1 , 0
  3178.3    .035       0  3493.4    .045       0  3600.6     .07       0
  3651.4     .07       0  3655.7     .07       0  3927.1    .045       0
  4049.1     .07       0  4106.9    .045       0  4421.1     .07       0
  5361.3    .045       0  5512.3    .035       0  5581.5    .045       0
Bank Sta=3651.4,3655.7
XS Rating Curve= 0 ,0
Exp/Cntr=0.3,0.1

Type RM Length L Ch R = 1 ,43276   ,1036,1036,1036
BEGIN DESCRIPTION:
Long Branch 81.0
END DESCRIPTION:
XS GIS Cut Line= 3
        1345405.        6839288.      1347225.16      6837888.32
      1348159.64      6835973.03
#Sta/Elev= 30
  2703.9 2410.05  2839.8 2410.54    3224 2408.88  3296.6 2409.98  3373.5 2408.24
  3464.7 2408.62  3510.4 2406.94  3605.6 2406.62    3937 2403.76  4465.5 2404.02
    4480  2403.2  4483.6 2401.77    4484 2401.27    4489 2401.77  4507.8 2404.21
  4864.2 2403.15  5709.6 2404.14  5817.1 2403.91  5970.5  2404.4  6010.9 2406.34
    6024 2404.87  6033.4 2406.72  6046.3 2406.83    6056 2404.77  6068.5 2406.18
  6517.7 2409.08  6697.9 2411.67  7018.9 2412.83  7047.7 2414.08  7131.1 2413.59
#Mann= 9 ,-1 , 0
  2703.9    .045       0  3464.7     .07       0  3605.6    .035       0
    3937     .07       0  4483.6     .07       0    4489     .07       0
  5709.6    .045       0  5817.1    .035       0  5970.5    .045       0
Bank Sta=4483.6,4489
XS Rating Curve= 0 ,0
Exp/Cntr=0.3,0.1

Type RM Length L Ch R = 1 ,42240   ,148,148,148
BEGIN DESCRIPTION:
Long Branch 80.0
END DESCRIPTION:
XS GIS Cut Line= 3
      1347223.39      6839581.02      1347521.39      6838604.79
      1347999.89      6836457.04
#Sta/Elev= 30
  3979.3 2410.09    4780 2406.31    5358 2405.89  5581.6  2405.1  5734.4 2405.99
  5744.6 2405.49  5762.4    2402  5762.8  2401.5  5767.8    2402  5772.8 2404.88
  5777.9 2402.63  5785.6 2405.75  5864.9 2404.03  6112.3 2404.47  6267.1 2404.51
  6281.8 2405.47  6417.4 2404.64    6466 2405.64  6509.5 2404.82  6514.6 2405.92
    6553 2405.07  6601.6 2407.56  6615.4 2404.48  6625.7 2404.97  6635.9 2407.63
  6650.2 2407.72  6666.7 2405.86  6676.9 2407.36  6755.1 2407.42  7200.4 2410.25
#Mann= 8 ,-1 , 0
  3979.3    .045       0    4780     .07       0    5358    .094       0
  5581.6     .07       0  5762.4     .07       0  5767.8     .07       0
  6112.3    .035       0  6755.1    .045       0
Bank Sta=5762.4,5767.8
XS Rating Curve= 0 ,0
Exp/Cntr=0.3,0.1

Type RM Length L Ch R = 1 ,42092   ,303,303,303
BEGIN DESCRIPTION:
Long Branch 79.0
END DESCRIPTION:
XS GIS Cut Line= 3
      1347423.57      6839542.41      1347636.54      6838688.67
      1348389.07      6836521.72
#Sta/Elev= 30
  4120.1 2409.32  4396.2 2407.48  4454.5 2407.75    4520 2406.69  4578.1 2407.53
    4609 2406.12  5163.5 2405.97  5375.4  2406.2  5492.6 2406.55  5739.3 2406.52
  5786.1 2407.18  5837.9 2407.68  5847.6 2405.86  5855.5 2401.76  5855.9 2401.26
  5860.9 2401.76  5869.1 2403.08  5879.3 2407.14  5911.1 2406.18  5953.6 2406.79
  6334.5 2406.72  6444.5 2408.36  6594.8 2408.56    6657 2410.01  6719.2  2409.3
  6863.8 2409.88  6874.8 2410.93  6954.7  2411.6    7232 2412.57  7293.9 2412.78
#Mann= 10 ,-1 , 0
  4120.1    .035       0  5163.5    .094       0  5375.4    .035       0
  5492.6    .045       0  5786.1    .035       0  5855.5    .035       0
  5860.9    .035       0  5953.6    .045       0  6954.7    .035       0
    7232    .045       0
Bank Sta=5855.5,5860.9
XS Rating Curve= 0 ,0
Exp/Cntr=0.3,0.1

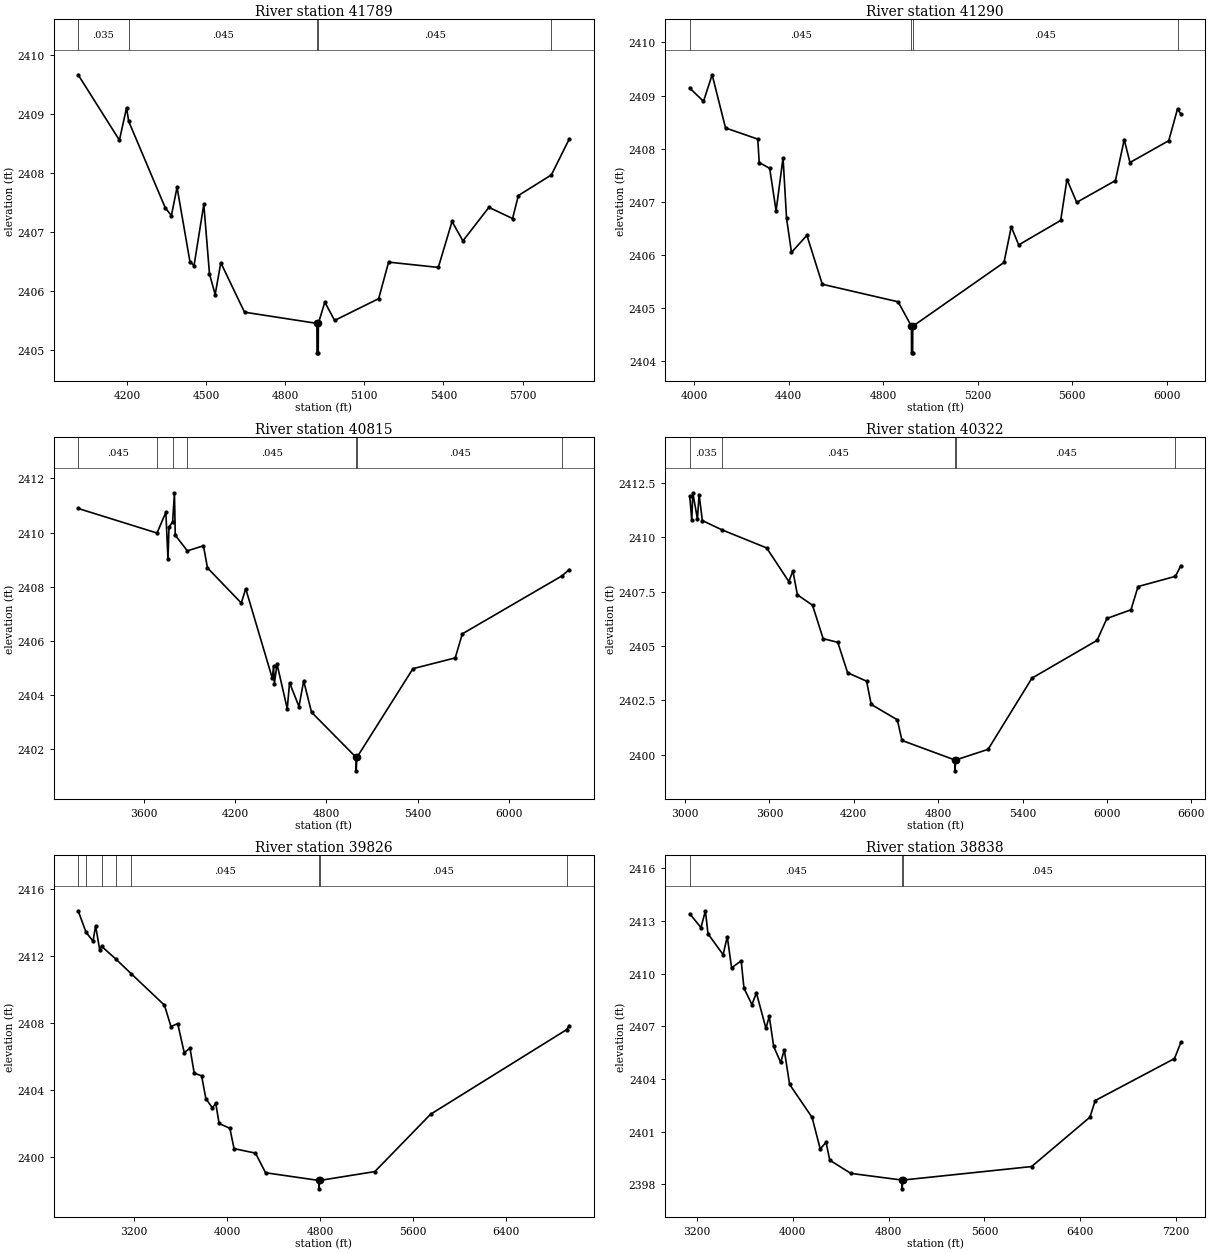
Type RM Length L Ch R = 1 ,41789   ,499,499,499
BEGIN DESCRIPTION:
Long Branch 78.0
END DESCRIPTION:
XS GIS Cut Line= 3
      1347407.77      6839642.77       1347907.3      6838793.83
      1348261.78      6837991.33
#Sta/Elev= 30
    4015 2409.67  4171.4 2408.56  4198.6 2409.11  4206.6 2408.88  4345.4 2407.41
  4368.6 2407.28    4390 2407.76  4438.8  2406.5  4454.4 2406.43  4491.5 2407.47
    4513 2406.29  4534.5 2405.94  4555.9 2406.48  4645.8 2405.64  4920.3 2405.45
  4920.8 2404.95  4925.4 2404.95  4925.8 2405.45  4950.4 2405.81  4987.5  2405.5
  5154.6 2405.87  5192.2 2406.49  5380.7  2406.4  5432.8 2407.18    5474 2406.85
  5572.6 2407.42  5662.3 2407.23  5684.2 2407.62  5809.4 2407.97  5877.3 2408.58
#Mann= 5 ,-1 , 0
    4015    .035       0  4206.6    .045       0  4920.3    .045       0
  4925.8    .045       0  5809.4    .035       0
Bank Sta=4920.3,4925.8
XS Rating Curve= 0 ,0
Exp/Cntr=0.3,0.1

Type RM Length L Ch R = 1 ,41290   ,475,475,475
BEGIN DESCRIPTION:
Long Branch 77.0
END DESCRIPTION:
XS GIS Cut Line= 3
      1347467.67      6839671.41       1348298.5      6839081.25
      1348532.72      6838047.97
#Sta/Elev= 30
  3980.9 2409.14    4039 2408.89  4075.7 2409.39  4132.3 2408.39  4268.8 2408.18
  4274.9 2407.74  4319.2 2407.63  4346.3 2406.83  4375.8 2407.83  4390.6 2406.69
  4411.5 2406.05  4476.7 2406.37  4541.9 2405.45  4862.9 2405.12  4919.2 2404.66
  4919.6 2404.16  4924.3 2404.16  4924.7 2404.66  5310.9 2405.86  5341.7 2406.53
  5373.1 2406.19  5550.8 2406.65  5577.5 2407.42  5618.6 2406.99  5782.6  2407.4
  5819.8 2408.17  5844.1 2407.74  6008.2 2408.15  6045.5 2408.75  6059.5 2408.65
#Mann= 4 ,-1 , 0
  3980.9    .045       0  4919.2    .045       0  4924.7    .045       0
  6045.5    .035       0
Bank Sta=4919.2,4924.7
XS Rating Curve= 0 ,0
Exp/Cntr=0.3,0.1

Type RM Length L Ch R = 1 ,40815   ,493,493,493
BEGIN DESCRIPTION:
Long Branch 76.0
END DESCRIPTION:
XS GIS Cut Line= 3
      1346755.03      6839887.99      1348534.97      6839468.07
      1348705.88       6838085.4
#Sta/Elev= 30
  3171.2 2410.89  3688.6 2409.98  3746.5 2410.75  3760.5 2409.01  3767.1 2410.19
    3791  2410.4  3802.9 2411.47  3808.2  2409.9  3887.6 2409.32  3993.1 2409.51
  4019.6 2408.69  4241.5 2407.39  4270.5 2407.92  4445.2  2404.6  4453.1 2405.05
  4458.3  2404.4    4476 2405.13  4542.9 2403.48  4558.2 2404.44  4619.9 2403.56
  4650.7 2404.51  4702.1 2403.35  4994.6 2401.68  4995.1 2401.18  5000.2 2401.68
  5367.5 2404.96  5644.9 2405.36  5691.7 2406.25  6346.7  2408.4  6393.2 2408.63
#Mann= 7 ,-1 , 0
  3171.2    .045       0  3688.6    .094       0    3791    .035       0
  3887.6    .045       0  4994.6    .045       0  5000.2    .045       0
  6346.7    .035       0
Bank Sta=4994.6,5000.2
XS Rating Curve= 0 ,0
Exp/Cntr=0.3,0.1

Type RM Length L Ch R = 1 ,40322   ,496,496,496
BEGIN DESCRIPTION:
Long Branch 75.0
END DESCRIPTION:
XS GIS Cut Line= 3
      1347155.04      6840487.98      1348953.31      6839692.15
      1349122.86       6838175.5
#Sta/Elev= 30
  3033.5  2411.9  3047.8  2410.8  3055.3 2412.06  3088.1 2410.85  3099.9 2411.98
  3123.2 2410.78    3260 2410.36  3580.2 2409.52  3738.2 2407.97    3767 2408.46
  3798.9 2407.36  3906.7 2406.88  3982.1 2405.34  4086.2 2405.17  4156.1 2403.77
    4291 2403.38  4323.9 2402.31  4509.8  2401.6  4542.6 2400.65    4919 2399.75
  4919.5 2399.25  4924.7 2399.75  5155.2 2400.24    5467 2403.52  5929.9 2405.26
  6000.3 2406.27  6171.4 2406.67  6221.7 2407.74  6487.2 2408.21  6526.1  2408.7
#Mann= 5 ,-1 , 0
  3033.5    .035       0    3260    .045       0    4919    .045       0
  4924.7    .045       0  6487.2    .035       0
Bank Sta=4919,4924.7
XS Rating Curve= 0 ,0
Exp/Cntr=0.3,0.1

Type RM Length L Ch R = 1 ,39826   ,988,988,988
BEGIN DESCRIPTION:
Long Branch 74.0
END DESCRIPTION:
XS GIS Cut Line= 3
        1347355.        6841488.      1349138.19      6840071.39
      1350098.88      6838386.42
#Sta/Elev= 30
  2722.6 2414.72  2790.5 2413.43  2850.3 2412.91  2872.4 2413.82  2907.6 2412.39
  2923.8  2412.6  3049.3 2411.82  3178.7 2410.96  3463.4 2409.09  3519.6 2407.81
  3577.3 2407.99  3633.3 2406.26    3683 2406.52  3718.8 2405.04  3782.6 2404.87
  3819.2 2403.51  3875.2 2402.96  3904.1 2403.23  3932.9 2402.03  4025.3 2401.74
  4061.1 2400.53  4245.3 2400.26  4331.8 2399.09  4790.3 2398.63  4790.8 2398.13
    4796 2398.63  5270.3 2399.16  5748.5 2402.58  6917.5 2407.63  6939.6 2407.87
#Mann= 8 ,-1 , 0
  2722.6    .035       0  2790.5     .07       0  2923.8    .045       0
  3049.3     .07       0  3178.7    .045       0  4790.3    .045       0
    4796    .045       0  6917.5    .035       0
Bank Sta=4790.3,4796
XS Rating Curve= 0 ,0
Exp/Cntr=0.3,0.1

Type RM Length L Ch R = 1 ,38838   ,499,499,499
BEGIN DESCRIPTION:
Long Branch 73.0
END DESCRIPTION:
XS GIS Cut Line= 3
      1347755.03      6841837.98      1349357.84      6840893.87
      1350355.02      6838887.96
#Sta/Elev= 30
  3139.8 2413.41  3233.4 2412.62  3270.5 2413.58    3292 2412.27  3418.3 2411.08
  3453.1  2412.1  3489.2 2410.33  3569.2 2410.73  3592.4 2409.17  3659.1 2408.24
  3696.2  2408.9  3776.2 2406.88  3803.5 2407.57  3840.6 2405.85  3899.1 2404.94
    3929 2405.65  3973.4 2403.69  4161.1 2401.81  4229.1 2400.01  4277.8 2400.39
  4309.1 2399.37  4484.8 2398.62  4912.3 2398.24  4912.8 2397.74  4918.6 2398.24
  5994.1 2399.01  6480.7 2401.82  6525.3 2402.77  7186.8 2405.16  7240.1 2406.08
#Mann= 3 ,-1 , 0
  3139.8    .045       0  4912.3    .045       0  4918.6    .045       0
Bank Sta=4912.3,4918.6
XS Rating Curve= 0 ,0
Exp/Cntr=0.3,0.1

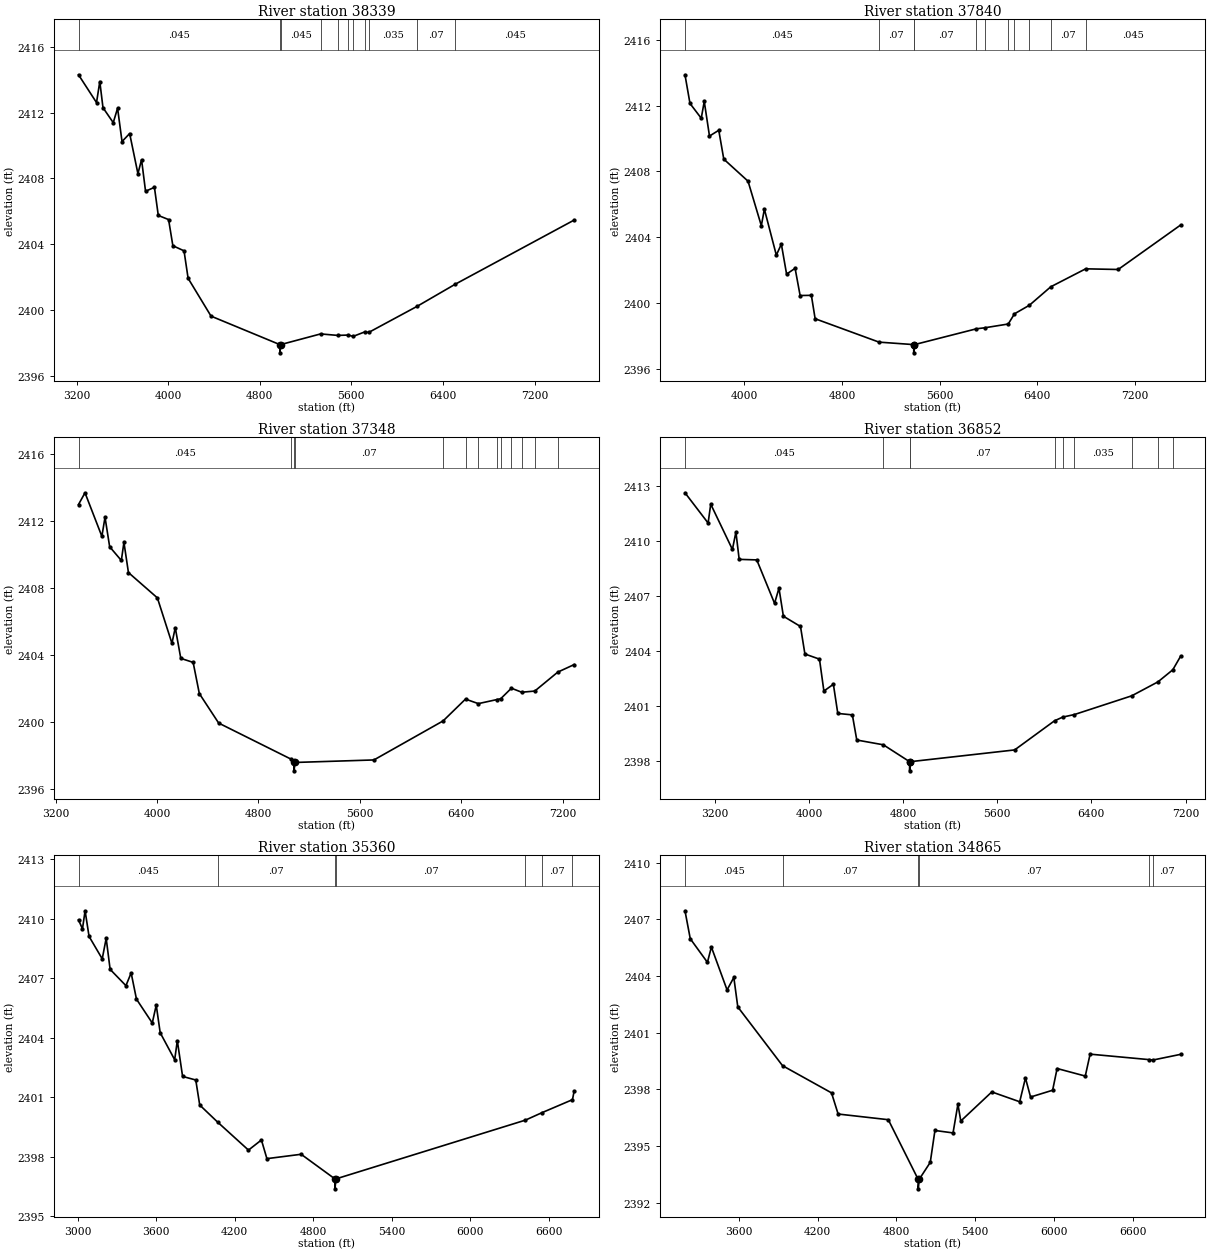
Type RM Length L Ch R = 1 ,38339   ,499,499,499
BEGIN DESCRIPTION:
Long Branch 72.0
END DESCRIPTION:
XS GIS Cut Line= 3
        1347905.        6842088.      1349491.35      6841274.67
      1351305.02      6839487.98
#Sta/Elev= 30
  3217.3  2414.3  3374.6 2412.61  3403.2 2413.89    3431  2412.3  3520.7 2411.39
  3558.5 2412.27  3597.3 2410.24  3663.9 2410.73  3736.1 2408.29  3767.9 2409.14
  3802.7 2407.22  3880.3 2407.46    3914 2405.75  4003.9  2405.5  4041.3 2403.91
  4138.8  2403.6  4174.4 2401.93  4374.8 2399.63  4975.7  2397.9  4976.2  2397.4
  4982.1  2397.9  5331.6 2398.55  5480.1 2398.46    5573 2398.48  5615.8  2398.4
  5716.1 2398.67  5751.5 2398.64  6172.7 2400.22  6507.1 2401.57  7545.9 2405.47
#Mann= 11 ,-1 , 0
  3217.3    .045       0  4975.7    .045       0  4982.1    .045       0
  5331.6     .07       0  5480.1    .035       0    5573     .07       0
  5615.8    .035       0  5716.1     .07       0  5751.5    .035       0
  6172.7     .07       0  6507.1    .045       0
Bank Sta=4975.7,4982.1
XS Rating Curve= 0 ,0
Exp/Cntr=0.3,0.1

Type RM Length L Ch R = 1 ,37840   ,492,492,492
BEGIN DESCRIPTION:
Long Branch 71.0
END DESCRIPTION:
XS GIS Cut Line= 3
        1348105.        6842038.      1349554.57      6841706.49
      1351155.01      6839687.99
#Sta/Elev= 30
    3513 2413.87    3554 2412.13  3646.4 2411.23    3671 2412.25  3713.9 2410.15
    3790  2410.5    3831 2408.75  4029.9 2407.41  4138.8 2404.71  4163.9 2405.71
  4261.9 2402.92    4303 2403.59  4345.9 2401.77  4415.7 2402.12  4456.8 2400.47
  4549.1 2400.48  4579.9 2399.06  5103.6 2397.64  5387.9 2397.49  5388.4 2396.99
  5394.4 2397.49  5902.3 2398.45  5969.6 2398.51  6162.8 2398.74  6214.1 2399.36
  6336.4 2399.88  6511.6    2401  6797.4 2402.09    7064 2402.05    7576 2404.75
#Mann= 11 ,-1 , 0
    3513    .045       0  5103.6     .07       0  5387.9    .045       0
  5394.4     .07       0  5902.3    .035       0  5969.6     .07       0
  6162.8    .035       0  6214.1     .07       0  6336.4    .035       0
  6511.6     .07       0  6797.4    .045       0
Bank Sta=5387.9,5394.4
XS Rating Curve= 0 ,0
Exp/Cntr=0.3,0.1

Type RM Length L Ch R = 1 ,37348   ,496,496,496
BEGIN DESCRIPTION:
Long Branch 70.0
END DESCRIPTION:
XS GIS Cut Line= 3
      1348254.97      6842338.01      1349836.75      6841988.19
      1351255.03      6840187.96
#Sta/Elev= 30
    3380 2412.98  3431.2 2413.68  3564.4 2411.08  3589.2 2412.22  3625.8 2410.46
    3718 2409.64  3738.5 2410.72    3774 2408.92  4002.4 2407.41  4117.4  2404.7
  4143.6 2405.63  4187.2  2403.8  4284.7 2403.56  4333.5  2401.7  4486.1 2399.94
  5059.5 2397.78  5080.9 2397.59  5081.4 2397.09  5088.1 2397.59  5711.5 2397.74
  6257.7 2400.07  6434.2 2401.37  6535.6  2401.1  6680.8 2401.34  6711.8 2401.39
  6796.4 2402.02  6877.9 2401.78  6980.9 2401.85  7162.4 2402.98  7291.8 2403.43
#Mann= 13 ,-1 , 0
    3380    .045       0  5059.5     .07       0  5080.9    .045       0
  5088.1     .07       0  6257.7    .035       0  6434.2     .07       0
  6535.6    .035       0  6680.8     .07       0  6711.8    .035       0
  6796.4     .07       0  6877.9    .035       0  6980.9     .07       0
  7162.4    .045       0
Bank Sta=5080.9,5088.1
XS Rating Curve= 0 ,0
Exp/Cntr=0.3,0.1

Type RM Length L Ch R = 1 ,36852   ,1492,1492,1492
BEGIN DESCRIPTION:
Long Branch 69.0
END DESCRIPTION:
XS GIS Cut Line= 3
      1348404.99      6843138.01      1350188.57      6842120.31
      1351405.03      6840337.96
#Sta/Elev= 30
  2946.5 2412.64  3143.1 2410.99  3165.3 2412.02  3349.5 2409.55  3379.3  2410.5
    3407 2409.01  3556.5 2408.98  3707.7 2406.61  3745.1 2407.44  3782.6 2405.91
    3928 2405.35  3965.5 2403.85  4089.3 2403.57  4126.8 2401.83  4207.4  2402.2
  4244.9 2400.61  4368.7 2400.53  4406.2 2399.16  4631.8  2398.9  4854.8 2397.98
  4855.3 2397.48    4862 2397.98  5747.5 2398.62  6086.7 2400.21  6156.2 2400.41
  6255.9 2400.55  6742.4 2401.57    6965 2402.33  7091.4 2402.99  7157.9 2403.73
#Mann= 10 ,-1 , 0
  2946.5    .045       0  4631.8     .07       0  4854.8     .07       0
    4862     .07       0  6086.7    .035       0  6156.2     .07       0
  6255.9    .035       0  6742.4     .07       0    6965    .035       0
  7091.4    .045       0
Bank Sta=4854.8,4862
XS Rating Curve= 0 ,0
Exp/Cntr=0.3,0.1

Type RM Length L Ch R = 1 ,35360   ,495,495,495
BEGIN DESCRIPTION:
Long Branch 68.0
END DESCRIPTION:
XS GIS Cut Line= 3
      1348755.01        6843088.      1350735.27      6842867.49
        1350955.        6841088.
#Sta/Elev= 30
  3007.5 2409.93  3037.7 2409.48  3057.8 2410.39    3088  2409.1  3188.6 2407.97
  3218.8    2409    3249 2407.44  3369.7 2406.62  3409.5 2407.26  3450.2 2405.94
  3570.9 2404.74  3601.1 2405.64  3631.3 2404.25    3742 2402.89  3762.1 2403.85
  3802.4 2402.05    3903 2401.87  3933.2 2400.61  4069.9 2399.75  4305.5 2398.34
  4404.5 2398.85  4446.3 2397.91  4707.9 2398.13  4965.9 2396.89  4966.4 2396.39
  4973.2 2396.89  6420.9 2399.85  6545.4 2400.22  6780.1 2400.88    6793 2401.32
#Mann= 7 ,-1 , 0
  3007.5    .045       0  4069.9     .07       0  4965.9     .07       0
  4973.2     .07       0  6420.9    .035       0  6545.4     .07       0
  6780.1    .035       0
Bank Sta=4965.9,4973.2
XS Rating Curve= 0 ,0
Exp/Cntr=0.3,0.1

Type RM Length L Ch R = 1 ,34865   ,496,496,496
BEGIN DESCRIPTION:
Long Branch 67.0
END DESCRIPTION:
XS GIS Cut Line= 3
      1349154.97        6843088.      1350955.41      6843283.28
        1351755.        6841488.
#Sta/Elev= 30
    3189 2407.46  3229.3 2405.98    3360 2404.73  3390.2 2405.54  3509.7 2403.27
  3561.2 2403.93  3591.4 2402.37  3932.3 2399.26  4305.5 2397.82  4355.8  2396.7
  4738.1  2396.4  4965.7 2393.24  4966.2 2392.74  4973.1 2393.24  5057.7 2394.14
  5093.4 2395.83  5231.3  2395.7  5268.5 2397.22  5290.4 2396.33  5526.6 2397.87
  5739.2 2397.35    5783 2398.61  5821.9  2397.6    5990 2397.96  6024.2 2399.11
  6238.8 2398.71  6275.6 2399.87  6725.4 2399.58  6755.2 2399.56  6965.3 2399.86
#Mann= 6 ,-1 , 0
    3189    .045       0  3932.3     .07       0  4965.7     .07       0
  4973.1     .07       0  6725.4    .035       0  6755.2     .07       0
Bank Sta=4965.7,4973.1
XS Rating Curve= 0 ,0
Exp/Cntr=0.3,0.1

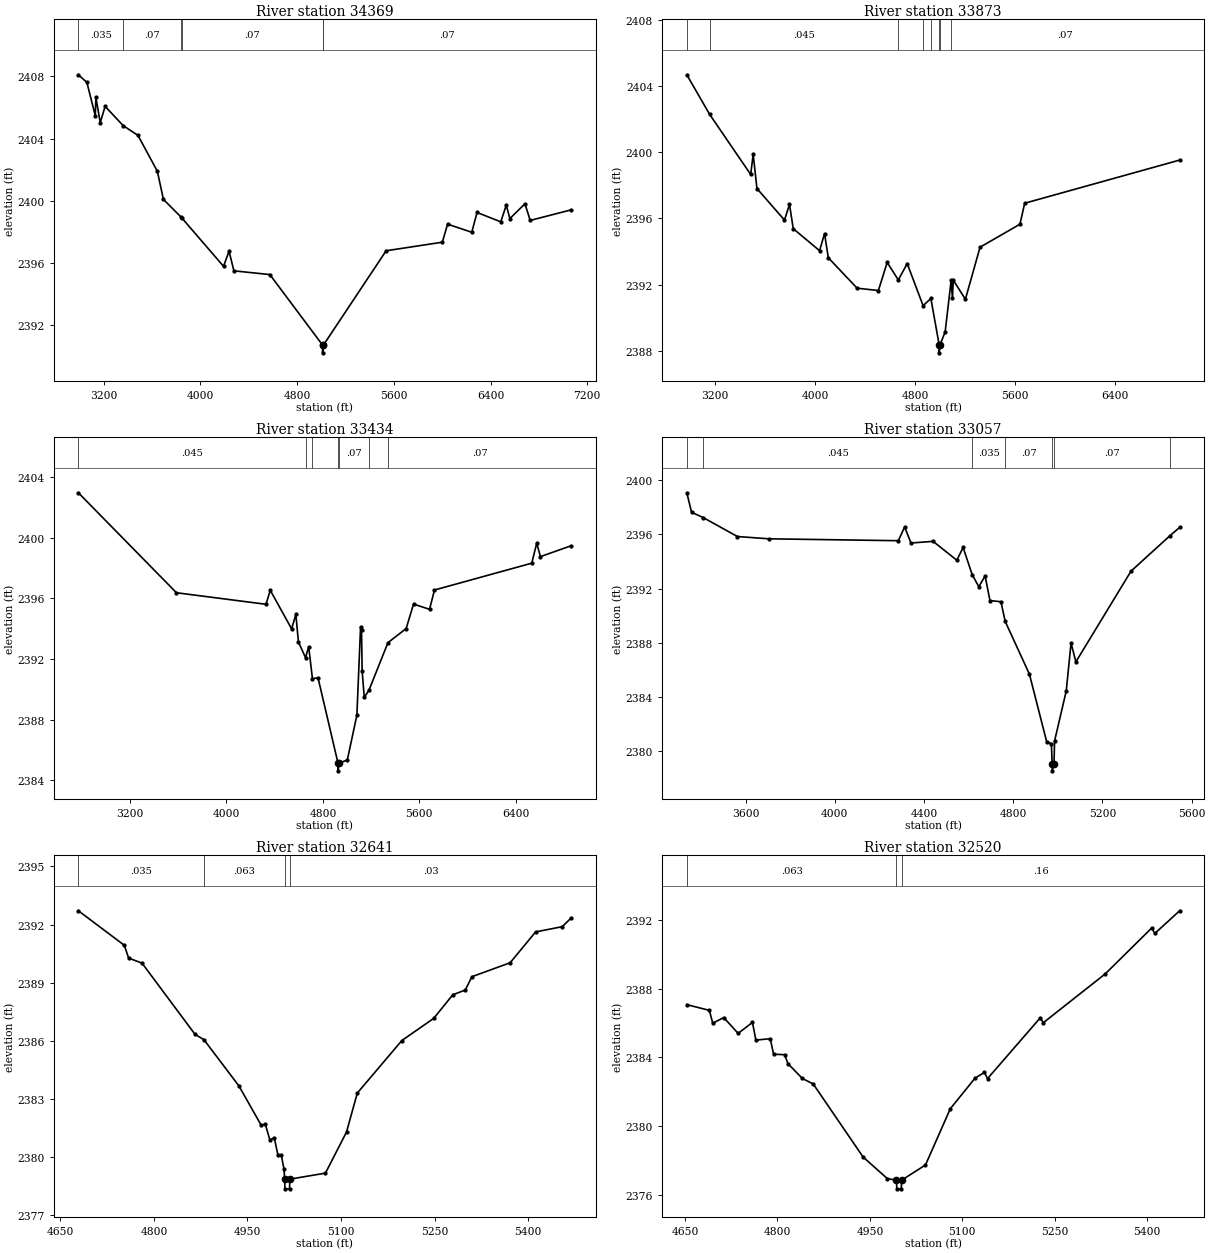
Type RM Length L Ch R = 1 ,34369   ,496,496,496
BEGIN DESCRIPTION:
Long Branch 66.0
END DESCRIPTION:
XS GIS Cut Line= 3
      1349054.97        6843538.      1351054.55      6843747.28
      1352055.02      6841937.96
#Sta/Elev= 30
  2989.5  2408.1  3059.9 2407.61  3129.4 2405.47  3134.5 2406.64  3170.5 2405.02
  3210.7 2406.07  3362.1 2404.82  3482.2 2404.21  3643.1  2401.9  3693.3 2400.09
  3842.6 2398.93  3843.1 2398.92  4190.7 2395.79  4236.3 2396.76  4276.5  2395.5
  4573.9 2395.26    5010 2390.73  5010.5 2390.23  5017.5 2390.73  5536.2 2396.79
  6001.1 2397.34  6044.6  2398.5  6244.7 2397.98  6288.6 2399.25  6484.7 2398.65
  6530.4 2399.72  6560.1 2398.86  6684.9 2399.81  6728.4 2398.74  7067.5 2399.42
#Mann= 6 ,-1 , 0
  2989.5    .035       0  3362.1     .07       0  3842.6    .045       0
  3843.1     .07       0    5010     .07       0  5017.5     .07       0
Bank Sta=5010,5017.5
XS Rating Curve= 0 ,0
Exp/Cntr=0.3,0.1

Type RM Length L Ch R = 1 ,33873   ,439,439,439
BEGIN DESCRIPTION:
Long Branch 65.0
END DESCRIPTION:
XS GIS Cut Line= 3
      1349304.95        6844088.      1351328.11      6844111.73
        1351905.        6842288.
#Sta/Elev= 30
  2976.7 2404.69  3158.5  2402.3  3486.8 2398.66  3506.8 2399.88  3536.8 2397.81
  3756.8  2395.9  3796.8 2396.85  3826.8 2395.38  4036.8 2394.05  4076.8 2395.08
  4106.8 2393.62  4336.8 2391.78  4506.9 2391.64  4576.9 2393.34    4666 2392.28
  4736.9 2393.27    4864 2390.72  4925.9 2391.16  4991.8 2388.37  4992.3 2387.87
    5000 2388.37    5040 2389.14  5087.9 2392.25  5098.3 2391.16  5104.6 2392.27
  5201.6 2391.11  5318.6 2394.26  5637.4 2395.65  5675.2 2396.92  6912.8 2399.53
#Mann= 8 ,-1 , 0
  2976.7     .07       0  3158.5    .045       0    4666    .035       0
    4864     .07       0  4925.9    .035       0  4991.8    .035       0
    5000    .035       0  5087.9     .07       0
Bank Sta=4991.8,5000
XS Rating Curve= 0 ,0
Exp/Cntr=0.3,0.1

Type RM Length L Ch R = 1 ,33434   ,377,377,377
BEGIN DESCRIPTION:
Long Branch 64.0
END DESCRIPTION:
XS GIS Cut Line= 3
      1350005.02      6845937.98      1351624.84      6844408.07
      1352004.99      6842588.05
#Sta/Elev= 30
  2771.9 2402.95  3585.2 2396.36    4328  2395.6  4363.6 2396.52  4540.4 2393.98
  4575.6 2394.93    4597 2393.12  4655.9 2392.08    4682  2392.8  4713.2  2390.7
  4759.7 2390.75  4925.4 2385.12  4925.9 2384.62  4933.7 2385.12  5002.6 2385.34
  5081.8 2388.29  5112.4 2394.11  5120.3 2393.89  5125.4 2391.21  5143.1 2389.46
  5182.2 2389.94  5339.6 2393.07  5490.4    2394  5551.7 2395.61  5684.5 2395.27
  5725.4 2396.54  6532.4 2398.31  6573.3 2399.63    6604 2398.74  6859.3 2399.46
#Mann= 7 ,-1 , 0
  2771.9    .045       0  4655.9    .035       0  4713.2     .07       0
  4925.4     .07       0  4933.7     .07       0  5182.2    .063       0
  5339.6     .07       0
Bank Sta=4925.4,4933.7
XS Rating Curve= 0 ,0
Exp/Cntr=0.3,0.1

Type RM Length L Ch R = 1 ,33057   ,416,416,416
BEGIN DESCRIPTION:
Long Branch 63.0
END DESCRIPTION:
XS GIS Cut Line= 3
      1350555.01      6845837.99      1351788.67      6844721.31
      1352060.64      6844247.52
#Sta/Elev= 30
    3336 2399.08  3357.3 2397.64  3410.4 2397.24  3562.7 2395.85    3704 2395.68
  4284.6 2395.54    4313 2396.56  4341.3 2395.37  4440.7 2395.49  4546.8  2394.1
  4575.2 2395.04  4615.7 2393.04  4645.5 2392.14  4673.9 2392.94  4695.5 2391.12
  4744.8 2391.03  4763.9 2389.58  4872.6 2385.68  4950.3 2380.67  4971.2 2380.55
  4974.5 2379.04    4975 2378.54  4982.8 2379.04  4985.4 2380.75  5037.7 2384.44
  5059.3 2387.98  5080.9 2386.59  5328.2 2393.29  5500.9 2395.88  5546.3 2396.52
#Mann= 7 ,-1 , 0
    3336     .07       0  3410.4    .045       0  4615.7    .035       0
  4763.9     .07       0  4974.5     .07       0  4982.8     .07       0
  5500.9    .063       0
Bank Sta=4974.5,4982.8
XS Rating Curve= 0 ,0
Exp/Cntr=0.3,0.1

Type RM Length L Ch R = 1 ,32641   ,121,121,121
BEGIN DESCRIPTION:
Long Branch 62.1
END DESCRIPTION:
XS GIS Cut Line= 3
      1351718.41      6845255.58      1351938.25      6845021.54
      1352033.61      6844562.13
#Sta/Elev= 30
  4678.9 2392.71  4752.6 2390.93  4759.5 2390.27    4781 2390.01  4865.9 2386.34
  4880.3 2386.06  4936.3 2383.68  4971.9 2381.66  4978.8 2381.69  4986.1 2380.88
    4993 2381.01    4999  2380.1  5004.3  2380.1  5008.7 2379.38  5009.7 2378.87
  5010.2 2378.37  5017.5 2378.37    5018 2378.87  5075.1 2379.18  5108.9  2381.3
  5126.2 2383.31  5197.7 2386.02  5248.7 2387.16  5279.4 2388.38  5299.3 2388.62
    5310 2389.31  5371.3 2390.03  5412.1 2391.62  5454.8 2391.89  5469.2 2392.34
#Mann= 4 ,-1 , 0
  4678.9    .035       0  4880.3    .063       0  5009.7     .03       0
    5018     .03       0
Bank Sta=5009.7,5018
XS Rating Curve= 0 ,0
Exp/Cntr=0.3,0.1

Type RM Length L Ch R = 1 ,32520   ,576,576,576
BEGIN DESCRIPTION:
Long Branch 62.0
END DESCRIPTION:
XS GIS Cut Line= 3
      1351914.89      6845355.77      1352054.97      6845038.08
      1352105.01      6844587.95
#Sta/Elev= 30
  4652.8 2387.06  4689.4 2386.73  4694.9 2385.98  4712.8 2386.31  4736.1 2385.39
  4759.4 2386.03  4764.9    2385  4788.2 2385.08  4793.7 2384.18  4811.5 2384.15
    4817 2383.63  4840.3 2382.77    4858 2382.45    4939  2378.2  4978.2 2376.95
  4993.2 2376.85  4993.7 2376.35    5001 2376.35  5001.5 2376.85  5040.3 2377.74
  5080.6 2381.01  5120.8 2382.79    5136 2383.12    5141 2382.76  5226.5 2386.29
  5231.6 2386.01  5332.1 2388.85  5407.6 2391.52  5412.6  2391.2  5452.9 2392.52
#Mann= 3 ,-1 , 0
  4652.8    .063       0  4993.2     .16       0  5001.5     .16       0
Bank Sta=4993.2,5001.5
XS Rating Curve= 0 ,0
Exp/Cntr=0.3,0.1