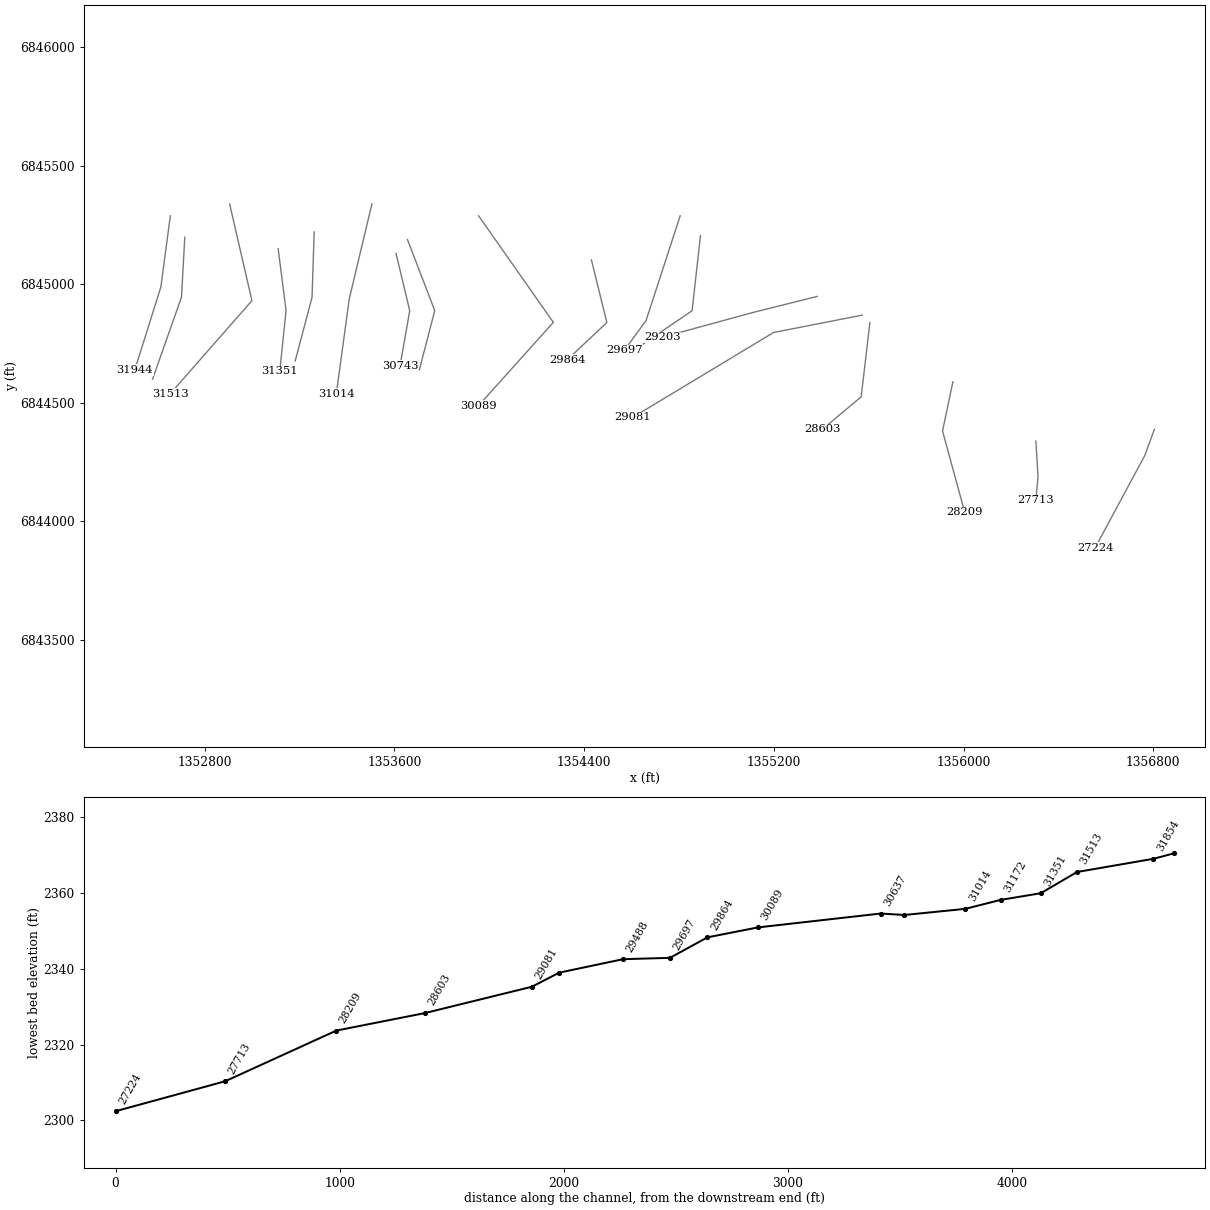
HEC-RAS study Long Branch.prj: Long Branch Base Level Engineering

--- Long Branch.g01 (geometry) --- (continued)

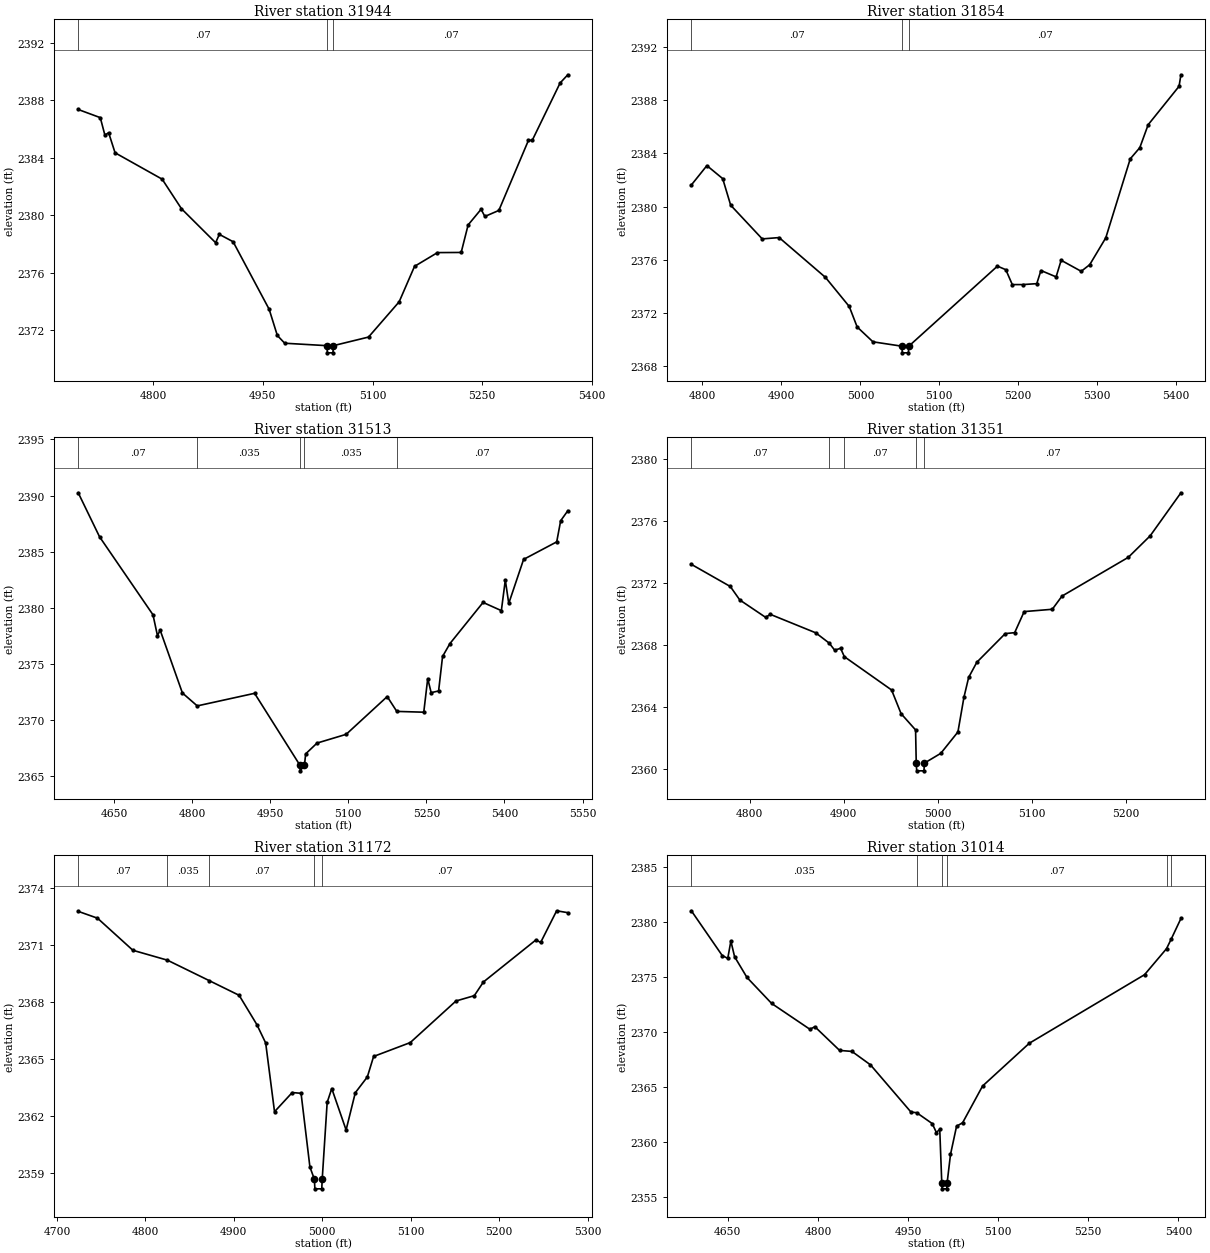
Type RM Length L Ch R = 1 ,31944   ,90,90,90
BEGIN DESCRIPTION:
Long Branch 61.0
END DESCRIPTION:
XS GIS Cut Line= 3
      1352654.99      6845287.96      1352615.05      6844988.11
        1352505.        6844638.
#Sta/Elev= 30
  4697.5 2387.37  4727.7  2386.8    4734 2385.58  4739.1 2385.75  4747.9 2384.35
  4812.3 2382.51  4838.7 2380.45  4885.4 2378.08  4890.5 2378.66  4909.3 2378.15
  4958.6 2373.44  4969.8 2371.61  4979.9 2371.07  5037.7  2370.9  5038.2  2370.4
  5045.9  2370.4  5046.4  2370.9  5094.5  2371.5  5136.4 2373.96  5157.4 2376.43
  5188.8 2377.39  5221.2  2377.4  5230.7 2379.32  5248.4 2380.41  5253.6 2379.91
  5272.7 2380.33  5313.2 2385.22  5318.4 2385.22  5356.5 2389.22    5367 2389.79
#Mann= 3 ,-1 , 0
  4697.5     .07       0  5037.7     .07       0  5046.4     .07       0
Bank Sta=5037.7,5046.4
XS Rating Curve= 0 ,0
Exp/Cntr=0.3,0.1

Type RM Length L Ch R = 1 ,31854   ,341,341,341
BEGIN DESCRIPTION:
Long Branch 60.1
END DESCRIPTION:
XS GIS Cut Line= 3
      1352715.94      6845197.69      1352701.95      6844944.68
      1352579.85       6844598.9
#Sta/Elev= 30
  4785.9 2381.62  4805.6 2383.08  4825.6  2382.1  4835.7  2380.1  4875.7 2377.56
  4897.1 2377.66  4955.8 2374.66  4985.9 2372.47  4995.9 2370.93  5015.9 2369.81
  5052.6 2369.48  5053.1 2368.98  5060.8 2368.98  5061.3 2369.48  5173.6 2375.51
  5184.2 2375.24  5192.4 2374.12  5205.5 2374.12  5223.4 2374.19  5228.7 2375.18
  5247.9  2374.7  5254.3 2375.95  5279.7 2375.12  5290.5 2375.62  5310.8 2377.64
  5341.8 2383.59  5353.9 2384.43  5364.5 2386.16  5403.6 2389.05    5406 2389.92
#Mann= 3 ,-1 , 0
  4785.9     .07       0  5052.6     .07       0  5061.3     .07       0
Bank Sta=5052.6,5061.3
XS Rating Curve= 0 ,0
Exp/Cntr=0.3,0.1

Type RM Length L Ch R = 1 ,31513   ,162,162,162
BEGIN DESCRIPTION:
Long Branch 60.0
END DESCRIPTION:
XS GIS Cut Line= 3
      1352905.01      6845337.97      1352999.08      6844930.18
      1352655.02      6844538.02
#Sta/Elev= 30
  4581.5 2390.25  4622.5 2386.33  4725.1 2379.39  4733.7 2377.53  4738.9 2378.02
  4781.6 2372.43  4810.1 2371.28  4920.2  2372.4  5007.3    2366  5007.8  2365.5
    5016    2366  5018.3 2367.01  5040.1 2367.97  5096.1 2368.75  5174.9 2372.11
  5193.3 2370.79  5245.1 2370.72  5252.7 2373.71  5259.3 2372.46  5273.6 2372.61
  5281.2 2375.68  5295.4 2376.83    5359 2380.49  5394.1 2379.76  5401.7 2382.48
  5408.3  2380.4  5436.8 2384.32  5500.4 2385.88    5508 2387.76  5521.7 2388.65
#Mann= 5 ,-1 , 0
  4581.5     .07       0  4810.1    .035       0  5007.3    .035       0
    5016    .035       0  5193.3     .07       0
Bank Sta=5007.3,5016
XS Rating Curve= 0 ,0
Exp/Cntr=0.3,0.1

Type RM Length L Ch R = 1 ,31351   ,179,179,179
BEGIN DESCRIPTION:
Long Branch 59.2
END DESCRIPTION:
XS GIS Cut Line= 3
      1353109.69      6845149.09      1353142.99      6844889.22
      1353116.46      6844632.28
#Sta/Elev= 30
    4738 2373.23  4779.4  2371.8  4789.5 2370.93  4816.9 2369.81    4822    2370
  4870.2 2368.81  4884.6 2368.14  4890.3 2367.69  4896.6 2367.81  4900.6 2367.27
  4950.8 2365.12  4960.9 2363.59  4976.3 2362.54    4977  2360.4  4977.5  2359.9
  4985.2  2359.9  4985.7  2360.4  5003.1 2361.03  5021.3 2362.41  5027.7 2364.65
  5032.7 2365.93  5041.4 2366.91  5071.6 2368.76  5081.6 2368.82  5091.7 2370.18
  5121.6 2370.33  5131.9 2371.18  5202.3 2373.68  5225.6 2375.07  5258.3 2377.85
#Mann= 5 ,-1 , 0
    4738     .07       0  4884.6    .035       0  4900.6     .07       0
    4977     .07       0  4985.7     .07       0
Bank Sta=4977,4985.7
XS Rating Curve= 0 ,0
Exp/Cntr=0.3,0.1

Type RM Length L Ch R = 1 ,31172   ,158,158,158
BEGIN DESCRIPTION:
Long Branch 59.1
END DESCRIPTION:
XS GIS Cut Line= 3
      1353261.57      6845219.79      1353252.53      6844944.04
      1353181.47      6844675.79
#Sta/Elev= 30
  4724.1 2372.76  4745.9  2372.4  4785.9 2370.71  4824.9 2370.19  4872.3 2369.11
    4906 2368.34    4926  2366.8    4936 2365.83    4946 2362.21    4966 2363.22
    4976 2363.18    4986  2359.3  4991.1 2358.65  4991.6 2358.15  4999.4 2358.15
  4999.9 2358.65  5005.5  2362.7  5010.7 2363.43  5026.9 2361.25  5037.3 2363.21
  5050.9 2364.04    5058 2365.12  5099.4 2365.85  5151.1 2368.04  5171.8 2368.32
  5182.1 2369.04  5241.6 2371.26  5246.8 2371.12  5264.9 2372.79  5277.5 2372.69
#Mann= 5 ,-1 , 0
  4724.1     .07       0  4824.9    .035       0  4872.3     .07       0
  4991.1     .07       0  4999.9     .07       0
Bank Sta=4991.1,4999.9
XS Rating Curve= 0 ,0
Exp/Cntr=0.3,0.1

Type RM Length L Ch R = 1 ,31014   ,271,271,271
BEGIN DESCRIPTION:
Long Branch 59.0
END DESCRIPTION:
XS GIS Cut Line= 3
      1353505.01      6845338.03      1353409.72      6844938.43
      1353354.99      6844537.95
#Sta/Elev= 30
  4589.2 2381.01  4640.6 2376.95  4649.8 2376.69    4655 2378.26  4661.2 2376.84
  4681.8 2374.96  4722.9  2372.6  4786.5 2370.26  4794.8 2370.49    4836 2368.34
  4856.5 2368.25  4887.4 2367.03  4954.9 2362.74  4964.3 2362.69  4990.2  2361.7
  4997.1 2360.89  5002.7 2361.18  5006.1 2356.28  5006.6 2355.78  5014.4 2355.78
  5014.9 2356.28  5020.6  2358.9  5030.7 2361.46  5040.8 2361.78    5074 2365.11
  5151.8 2368.99  5343.6 2375.21  5380.2 2377.57    5388 2378.44  5404.2 2380.31
#Mann= 6 ,-1 , 0
  4589.2    .035       0  4964.3     .07       0  5006.1     .07       0
  5014.9     .07       0  5380.2    .035       0    5388    .063       0
Bank Sta=5006.1,5014.9
XS Rating Curve= 0 ,0
Exp/Cntr=0.3,0.1

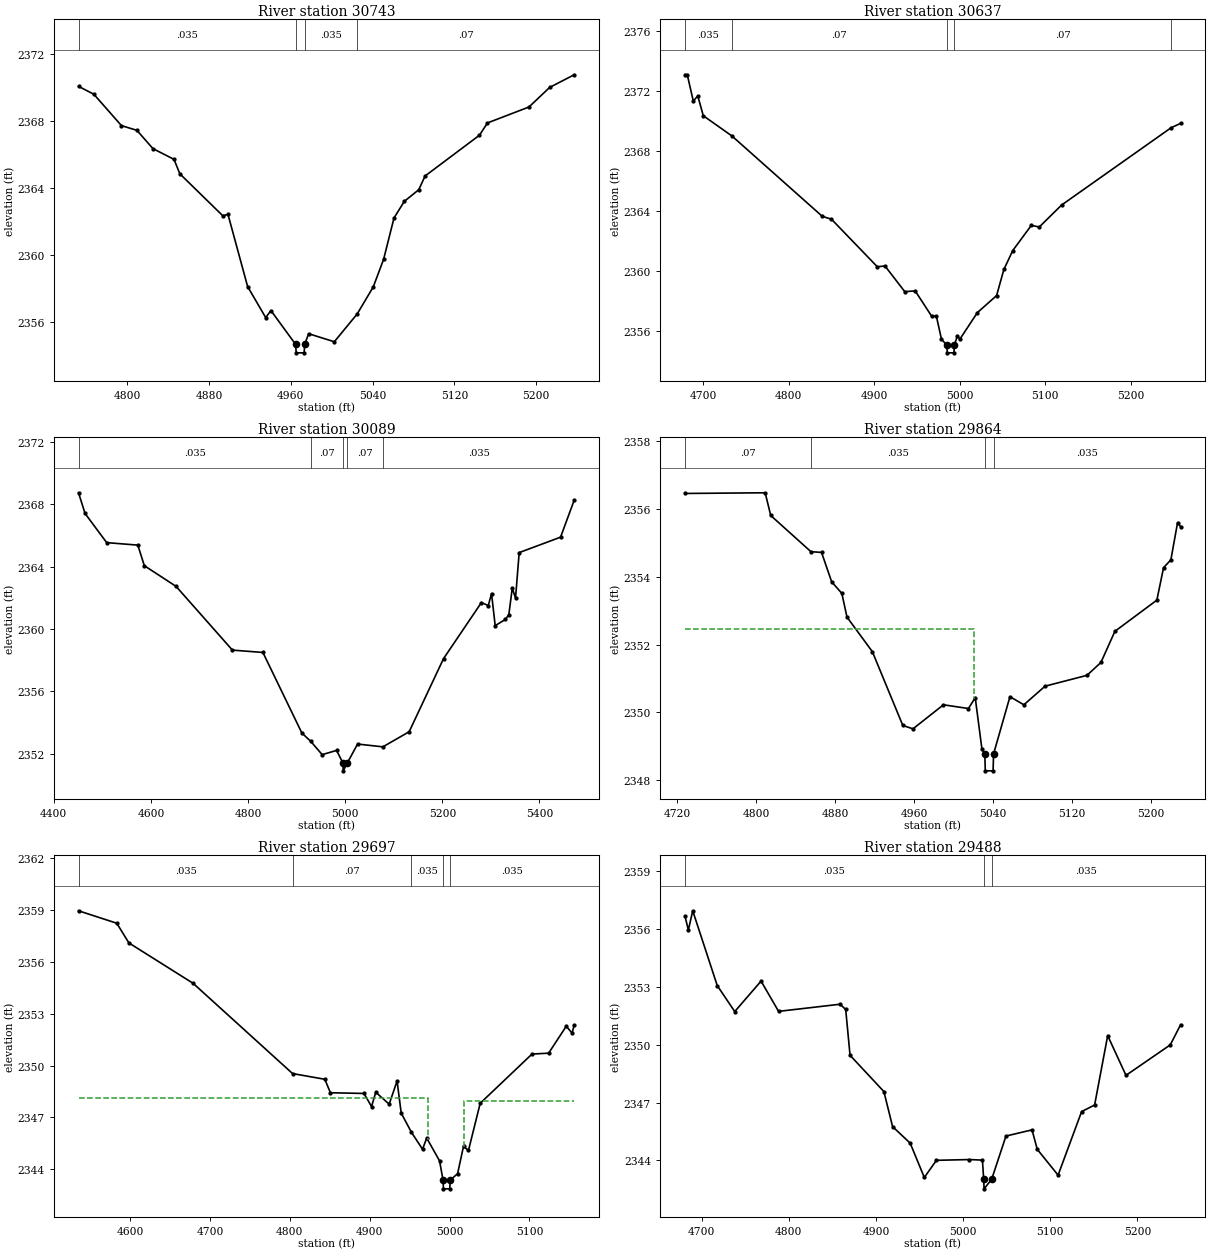
Type RM Length L Ch R = 1 ,30743   ,106,106,106
BEGIN DESCRIPTION:
Long Branch 58.1
END DESCRIPTION:
XS GIS Cut Line= 3
      1353606.78      6845128.84      1353664.54      6844887.97
      1353623.49      6844654.45
#Sta/Elev= 30
  4752.3 2370.05  4767.3 2369.58  4794.3 2367.71  4809.4 2367.43  4825.1 2366.34
  4845.7  2365.7  4851.4 2364.84  4893.4 2362.34  4898.5 2362.42  4917.7 2358.12
  4935.4 2356.27  4940.5 2356.69  4964.7 2354.67  4965.2 2354.17    4973 2354.17
  4973.5 2354.67  4977.4 2355.31  5002.5 2354.83  5024.9 2356.49  5040.6  2358.1
  5050.7 2359.74  5060.9 2362.21    5071  2363.2  5085.1 2363.89  5091.3 2364.71
  5144.5 2367.14  5152.3 2367.87  5192.9 2368.82  5213.2 2369.99  5237.1 2370.74
#Mann= 4 ,-1 , 0
  4752.3    .035       0  4964.7    .035       0  4973.5    .035       0
  5024.9     .07       0
Bank Sta=4964.7,4973.5
XS Rating Curve= 0 ,0
Exp/Cntr=0.3,0.1

Type RM Length L Ch R = 1 ,30637   ,548,548,548
BEGIN DESCRIPTION:
Long Branch 58.0
END DESCRIPTION:
XS GIS Cut Line= 3
        1353655.        6845188.      1353770.01      6844887.98
        1353705.        6844638.
#Sta/Elev= 30
  4678.7 2373.09  4681.4 2373.09  4688.4 2371.34  4693.7 2371.68  4700.1 2370.36
  4733.6 2369.01  4839.3 2363.65    4850 2363.46  4903.6 2360.29  4912.6 2360.34
  4935.7 2358.63  4947.9 2358.68  4967.3 2356.98  4972.6 2357.01  4978.6 2355.47
  4984.9 2355.05  4985.4 2354.55  4993.2 2354.55  4993.7 2355.05  4997.3  2355.7
    5000 2355.45  5020.6 2357.23  5043.1 2358.37  5051.6 2360.11    5062 2361.37
  5083.7 2363.05    5093 2362.94    5119  2364.4  5247.2 2369.56  5258.3 2369.85
#Mann= 5 ,-1 , 0
  4678.7    .035       0  4733.6     .07       0  4984.9     .07       0
  4993.7     .07       0  5247.2    .035       0
Bank Sta=4984.9,4993.7
XS Rating Curve= 0 ,0
Exp/Cntr=0.3,0.1

Type RM Length L Ch R = 1 ,30089   ,225,225,225
BEGIN DESCRIPTION:
Long Branch 57.0
END DESCRIPTION:
XS GIS Cut Line= 3
        1353955.        6845288.      1354270.21      6844838.51
        1353955.        6844488.
#Sta/Elev= 30
    4451 2368.74  4464.5 2367.41    4509 2365.54  4573.1 2365.38  4586.5 2364.06
  4651.9 2362.73  4767.8 2358.64  4830.6 2358.49  4910.8 2353.32  4929.2 2352.78
  4952.6 2351.93  4982.3  2352.2  4995.4 2351.39  4995.9 2350.89  5004.3 2351.39
  5025.5 2352.61  5077.6 2352.43  5131.7  2353.4  5202.4 2358.09  5280.4 2361.69
  5294.6  2361.5  5301.3 2362.27  5308.8 2360.21  5329.8 2360.61  5336.9 2360.92
    5344 2362.62  5350.7 2361.98  5358.2  2364.9  5443.4 2365.89  5471.4 2368.26
#Mann= 5 ,-1 , 0
    4451    .035       0  4929.2     .07       0  4995.4     .07       0
  5004.3     .07       0  5077.6    .035       0
Bank Sta=4995.4,5004.3
XS Rating Curve= 0 ,0
Exp/Cntr=0.3,0.1

Type RM Length L Ch R = 1 ,29864   ,167,167,167
BEGIN DESCRIPTION:
Long Branch 4353
END DESCRIPTION:
XS GIS Cut Line= 3
       1354430.6      6845102.35      1354495.91      6844837.99
      1354328.17      6844680.49
#Sta/Elev= 30
  4727.7 2356.46    4809 2356.48  4814.6 2355.81  4855.4 2354.74  4866.1 2354.72
  4876.4 2353.85  4886.7 2353.51  4891.9 2352.81  4917.6 2351.79  4948.5 2349.61
  4958.8 2349.51  4989.7 2350.22    5015 2350.11  5021.9 2350.43  5028.7 2348.91
  5031.6 2348.77  5032.1 2348.27    5040 2348.27  5040.5 2348.77  5057.1 2350.46
  5071.2 2350.22  5092.7 2350.77  5135.2 2351.09  5149.3 2351.47  5163.5 2352.39
    5206 2353.31  5212.8 2354.27  5220.2  2354.5    5227  2355.6  5230.1 2355.48
#Mann= 4 ,-1 , 0
  4727.7     .07       0  4855.4    .035       0  5031.6    .035       0
  5040.5    .035       0
#XS Ineff= 2 , 0
         5021.02 2352.47
Permanent Ineff=
       F       F
Bank Sta=5031.6,5040.5
XS Rating Curve= 0 ,0
Exp/Cntr=0.3,0.1

Type RM Length L Ch R = 1 ,29697   ,209,209,209
BEGIN DESCRIPTION:
Long Branch 56.0
END DESCRIPTION:
XS GIS Cut Line= 3
        1354805.      6845287.99      1354661.06      6844846.14
      1354569.14      6844719.97
#Sta/Elev= 30
  4535.3 2358.96  4583.2 2358.24  4598.4  2357.1  4678.9 2354.76  4803.4 2349.54
  4843.8 2349.21  4850.8 2348.43  4892.9 2348.39  4902.3 2347.63  4907.6 2348.46
  4924.4 2347.77  4934.3 2349.11  4939.5 2347.25  4952.3 2346.14  4966.2 2345.16
  4971.4 2345.81  4987.5 2344.49  4991.9 2343.37  4992.4 2342.87  5000.3 2342.87
  5000.8 2343.37  5010.1 2343.75  5017.5 2345.33  5023.7 2345.09  5038.4 2347.82
  5103.3 2350.67  5124.1 2350.72  5146.2 2352.28  5153.5 2351.88  5156.1 2352.35
#Mann= 5 ,-1 , 0
  4535.3    .035       0  4803.4     .07       0  4952.3    .035       0
  4991.9    .035       0  5000.8    .035       0
#XS Ineff= 2 , 0
         4972.59 2348.11 5018.07         2347.96
Permanent Ineff=
       F       F
Bank Sta=4991.9,5000.8
XS Rating Curve= 0 ,0
Exp/Cntr=0.3,0.1

Type RM Length L Ch R = 1 ,29488   ,285,285,285
BEGIN DESCRIPTION:
Long Branch 4354
END DESCRIPTION:
XS GIS Cut Line= 3
      1354890.66      6845204.75      1354855.18      6844887.63
      1354648.79      6844747.26
#Sta/Elev= 30
  4680.9 2356.67  4684.8 2355.95  4689.8 2356.95  4717.9 2353.07    4738 2351.72
  4768.2  2353.3  4788.3 2351.73  4858.8  2352.1  4865.3 2351.83  4870.3 2349.45
  4909.1 2347.57  4919.1 2345.75  4939.3 2344.89  4955.5 2343.11  4969.4    2344
  5007.2 2344.04  5022.2 2344.01  5023.6 2343.02  5024.1 2342.52  5032.8 2343.02
  5049.2 2345.26  5079.1 2345.58  5085.1 2344.57    5109 2343.23    5136 2346.53
  5150.9 2346.87  5165.9 2350.47  5186.9 2348.41  5237.7 2349.99  5249.6 2351.04
#Mann= 3 ,-1 , 0
  4680.9    .035       0  5023.6    .035       0  5032.8    .035       0
Bank Sta=5023.6,5032.8
XS Rating Curve= 0 ,0
Exp/Cntr=0.3,0.1

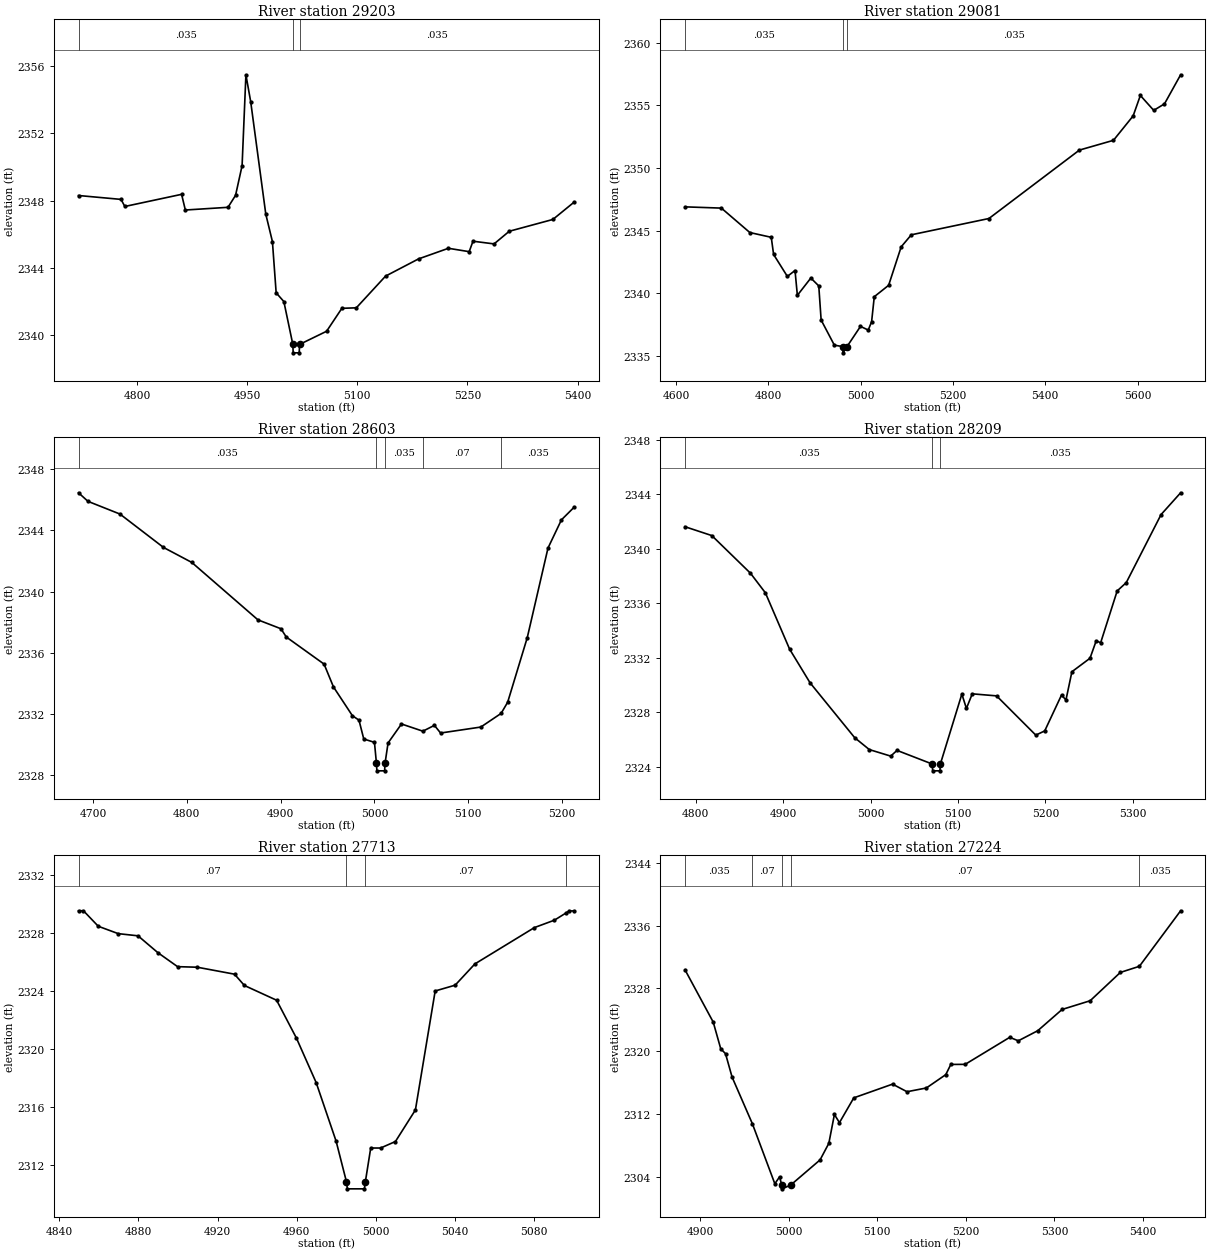
Type RM Length L Ch R = 1 ,29203   ,122,122,122
BEGIN DESCRIPTION:
Long Branch 55.1
END DESCRIPTION:
XS GIS Cut Line= 3
      1355382.51      6844947.96      1355111.16      6844880.12
      1354729.72      6844775.99
#Sta/Elev= 30
  4720.3  2348.3  4778.2 2348.07  4783.4 2347.65  4860.7 2348.37  4865.8 2347.44
  4923.9  2347.6  4934.2 2348.31  4943.1 2350.07  4948.3 2355.46  4954.8 2353.87
  4975.4 2347.19  4984.4 2345.57  4989.5 2342.53    5000 2342.01  5012.2 2339.47
  5012.7 2338.97  5020.9 2338.97  5021.4 2339.47  5058.2 2340.25    5079 2341.61
  5098.7 2341.64  5138.5 2343.52  5183.4 2344.54  5224.1 2345.17  5252.4 2344.97
  5257.6 2345.59  5286.3 2345.43    5307 2346.18  5366.4 2346.88  5395.4 2347.91
#Mann= 3 ,-1 , 0
  4720.3    .035       0  5012.2    .035       0  5021.4    .035       0
Bank Sta=5012.2,5021.4
XS Rating Curve= 0 ,0
Exp/Cntr=0.3,0.1

Type RM Length L Ch R = 1 ,29081   ,478,478,478
BEGIN DESCRIPTION:
Long Branch 55.0
END DESCRIPTION:
XS GIS Cut Line= 3
      1355572.74      6844869.05      1355198.84      6844795.88
      1354605.03      6844438.02
#Sta/Elev= 30
    4619  2346.9  4697.9  2346.8  4759.6 2344.85    4806 2344.47  4811.1  2343.1
  4840.9 2341.35  4857.5 2341.82  4862.6 2339.84  4891.8 2341.22    4909 2340.59
  4914.1 2337.87  4942.8 2335.86    4961 2335.75  4961.5 2335.25  4970.2 2335.75
  4999.4 2337.36  5016.2 2337.07  5023.5 2337.73  5029.3 2339.73  5060.4 2340.64
  5087.6 2343.71  5109.6 2344.67  5277.8 2345.97  5473.9 2351.43  5547.7 2352.21
  5590.4 2354.16    5606 2355.79    5635  2354.6  5658.3 2355.12  5693.3 2357.44
#Mann= 3 ,-1 , 0
    4619    .035       0    4961    .035       0  4970.2    .035       0
Bank Sta=4961,4970.2
XS Rating Curve= 0 ,0
Exp/Cntr=0.3,0.1

Type RM Length L Ch R = 1 ,28603   ,394,394,394
BEGIN DESCRIPTION:
Long Branch 54.0
END DESCRIPTION:
XS GIS Cut Line= 3
        1355605.        6844838.      1355568.32      6844524.64
      1355405.03      6844388.03
#Sta/Elev= 30
  4684.5 2346.46  4694.6  2345.9  4728.7 2345.07  4775.1 2342.89  4805.3 2341.91
  4875.8 2338.16  4900.3 2337.58    4906 2337.04  4946.3 2335.27  4956.3 2333.78
  4976.5  2331.9  4983.5 2331.61  4988.6 2330.38    5000 2330.16  5002.1  2328.8
  5002.6  2328.3  5010.8  2328.3  5011.3  2328.8  5014.5 2330.12  5028.8 2331.36
  5051.6 2330.89  5063.9 2331.27  5070.5 2330.77  5113.4 2331.16    5135 2332.05
    5142 2332.78  5162.9    2337    5185 2342.85  5199.3 2344.69  5212.9 2345.52
#Mann= 5 ,-1 , 0
  4684.5    .035       0  5002.1    .035       0  5011.3    .035       0
  5051.6     .07       0    5135    .035       0
Bank Sta=5002.1,5011.3
XS Rating Curve= 0 ,0
Exp/Cntr=0.3,0.1

Type RM Length L Ch R = 1 ,28209   ,496,496,496
BEGIN DESCRIPTION:
Long Branch 53.0
END DESCRIPTION:
XS GIS Cut Line= 3
      1355955.01      6844588.04      1355911.45      6844380.25
        1356005.      6844038.01
#Sta/Elev= 30
  4787.7 2341.61  4818.4 2340.96  4862.6  2338.2  4879.7 2336.76  4907.4 2332.63
  4930.8 2330.16  4981.9 2326.13  4998.6 2325.26  5023.1 2324.78  5030.3  2325.2
  5070.6  2324.2  5071.1  2323.7  5079.4  2323.7  5079.9  2324.2  5104.5 2329.33
  5109.7 2328.28  5116.4 2329.35  5144.2  2329.2  5189.1 2326.32  5199.3 2326.63
  5218.5 2329.26  5223.6  2328.9  5230.4 2330.97  5251.1 2331.96  5258.2 2333.24
  5263.3  2333.1  5282.2  2336.9  5292.6 2337.51  5332.4  2342.5  5354.8  2344.1
#Mann= 3 ,-1 , 0
  4787.7    .035       0  5070.6    .035       0  5079.9    .035       0
Bank Sta=5070.6,5079.9
XS Rating Curve= 0 ,0
Exp/Cntr=0.3,0.1

Type RM Length L Ch R = 1 ,27713   ,489,489,489
BEGIN DESCRIPTION:
Long Branch 52.0
END DESCRIPTION:
XS GIS Cut Line= 3
        1356305.      6844338.02      1356314.09      6844187.99
        1356305.      6844088.01
#Sta/Elev= 30
  4849.7 2329.55  4852.2 2329.55  4859.7 2328.48  4869.8 2327.97  4879.8 2327.82
  4889.8 2326.66  4899.8 2325.69  4909.8 2325.65  4928.6 2325.17  4933.6 2324.39
  4949.9 2323.37  4959.9 2320.76  4969.9 2317.68    4980 2313.63  4985.2 2310.84
  4985.7 2310.34  4994.3 2310.34  4994.8 2310.84  4997.5 2313.16  5002.5 2313.16
    5010 2313.61  5020.1 2315.79  5030.1 2324.01  5040.2 2324.41  5050.2 2325.88
  5080.3 2328.39  5090.4  2328.9  5096.3  2329.4  5097.9 2329.54  5100.4 2329.54
#Mann= 4 ,-1 , 0
  4849.7     .07       0  4985.2     .07       0  4994.8     .07       0
  5096.3    .035       0
Bank Sta=4985.2,4994.8
XS Rating Curve= 0 ,0
Exp/Cntr=0.3,0.1

Type RM Length L Ch R = 1 ,27224   ,498,498,498
BEGIN DESCRIPTION:
Long Branch 51.0
END DESCRIPTION:
XS GIS Cut Line= 3
      1356804.99      6844387.98      1356764.69      6844277.82
      1356555.02      6843888.03
#Sta/Elev= 30
  4882.7 2330.37  4914.6  2323.7  4923.1  2320.3  4928.5 2319.67  4935.9 2316.69
  4958.8 2310.75  4984.2 2303.09  4989.5 2303.96  4992.1 2302.94  4992.6 2302.44
  5002.3 2302.94  5035.3 2306.13  5045.2 2308.24  5051.5 2311.92  5057.2 2310.88
  5073.4 2314.04  5117.2 2315.79  5133.5 2314.82  5155.4  2315.3  5177.3    2317
    5183  2318.3  5199.2 2318.31  5249.6 2321.76  5259.2 2321.31  5281.2  2322.6
  5308.7 2325.31  5340.4 2326.42  5374.5 2330.03    5396 2330.81  5442.6 2337.89
#Mann= 5 ,-1 , 0
  4882.7    .035       0  4958.8     .07       0  4992.1     .07       0
  5002.3     .07       0    5396    .035       0
Bank Sta=4992.1,5002.3
XS Rating Curve= 0 ,0
Exp/Cntr=0.3,0.1