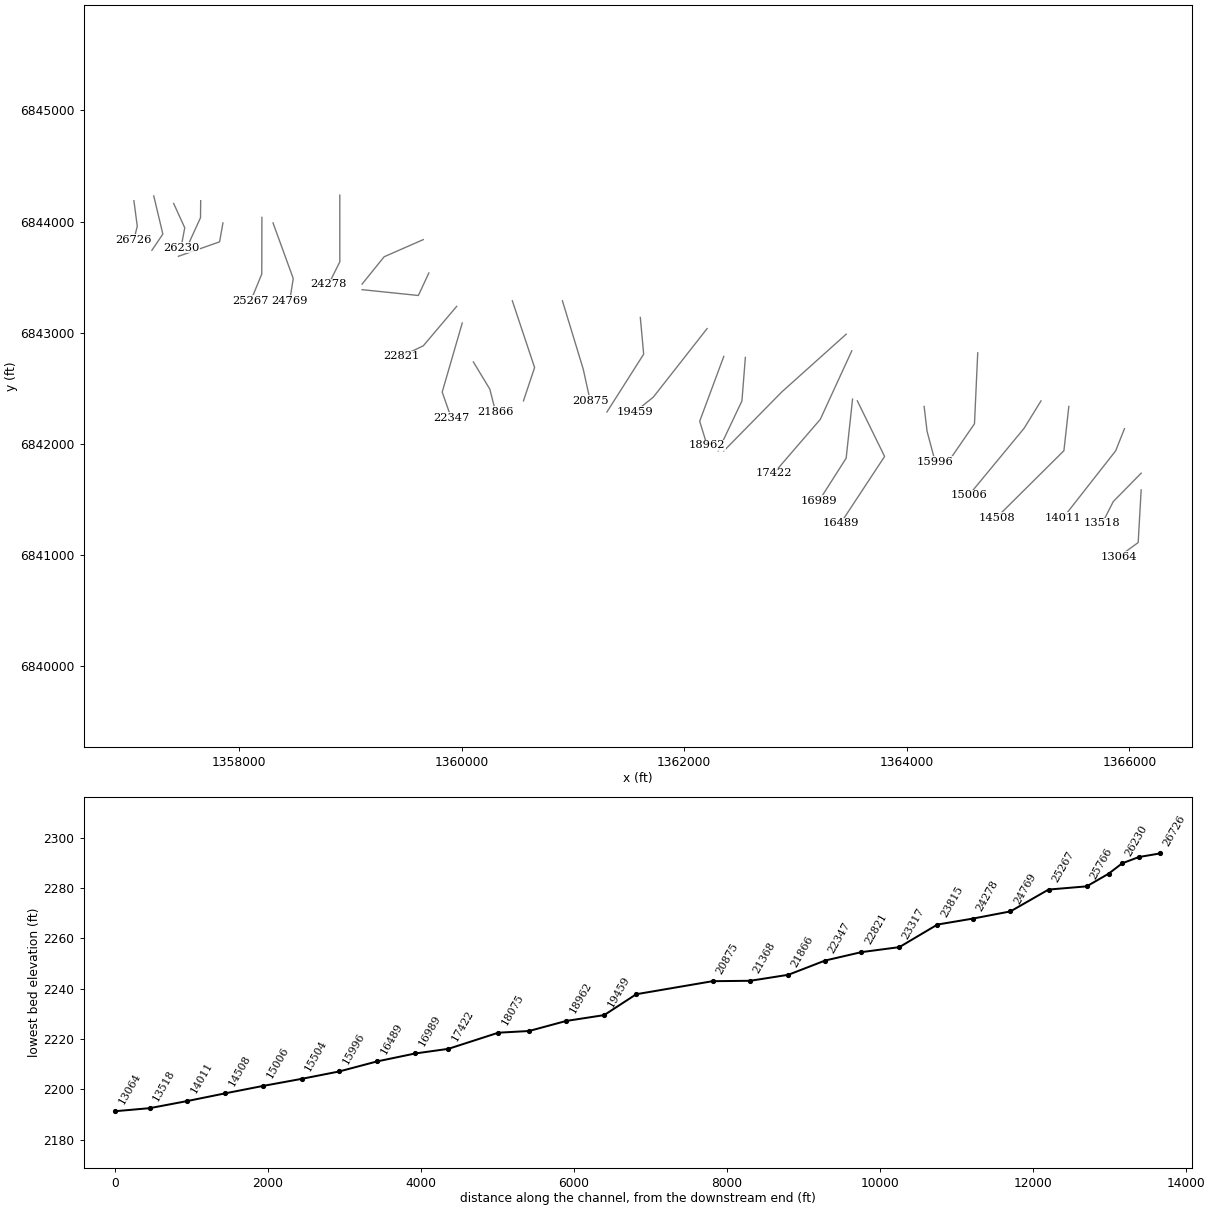
HEC-RAS study Long Branch.prj: Long Branch Base Level Engineering

--- Long Branch.g01 (geometry) --- (continued)

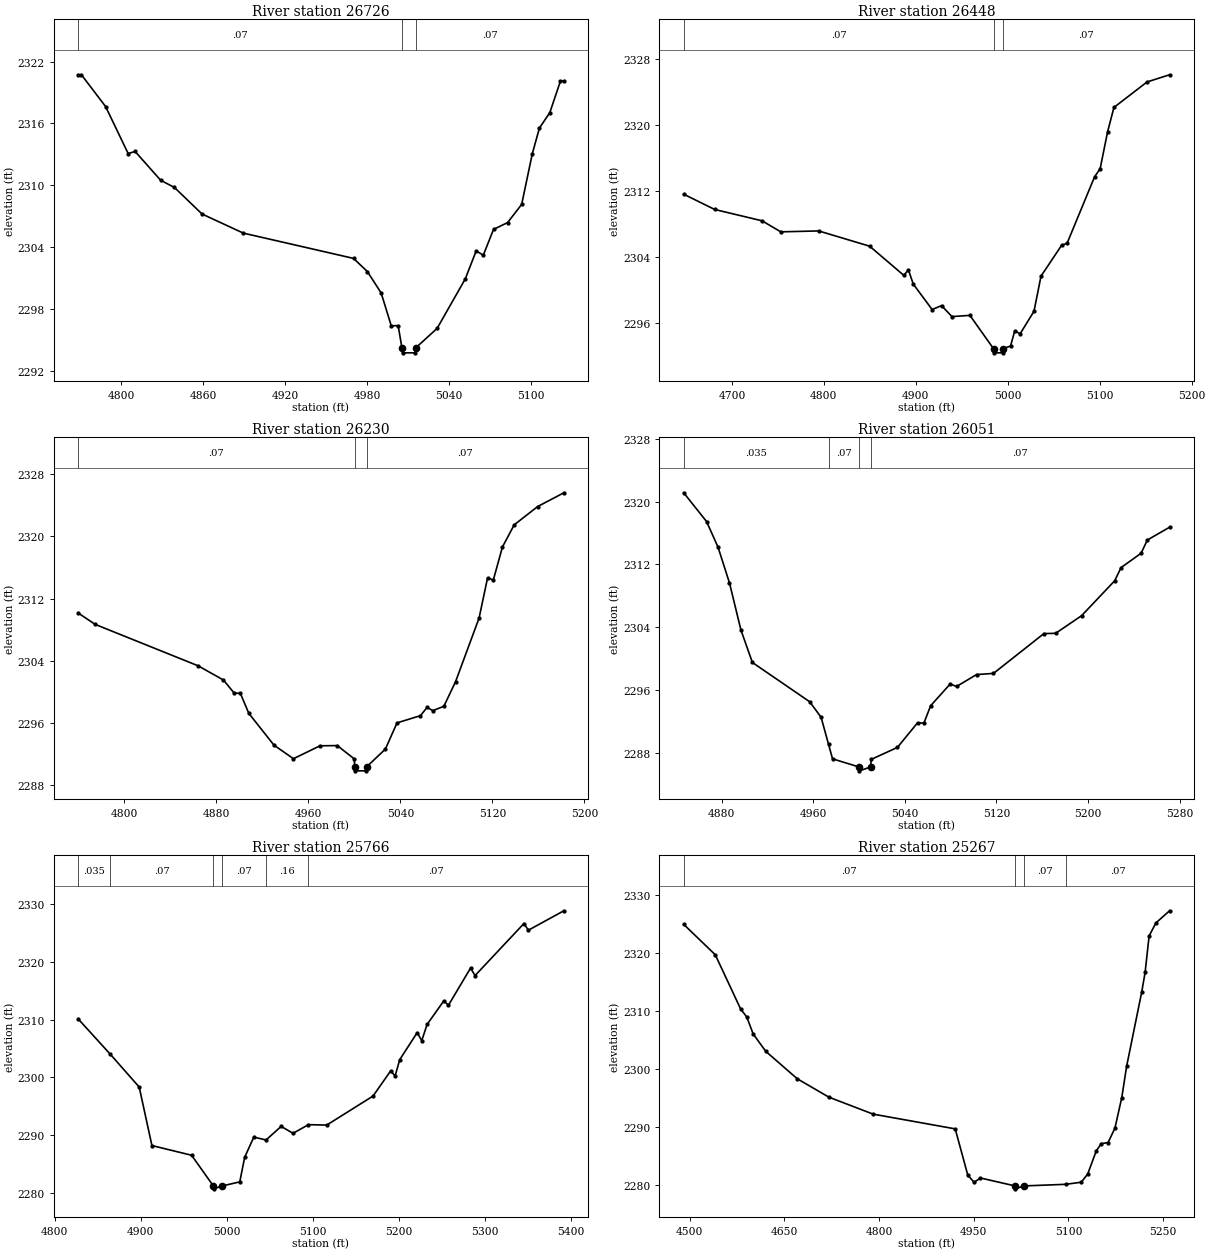
Type RM Length L Ch R = 1 ,26726   ,278,278,278
BEGIN DESCRIPTION:
Long Branch 50.0
END DESCRIPTION:
XS GIS Cut Line= 3
        1357055.      6844187.98      1357085.32      6843958.38
      1357055.01      6843838.03
#Sta/Elev= 30
  4768.4 2320.72  4770.9 2320.72  4788.6 2317.64  4805.1 2313.09  4810.2 2313.29
  4828.9  2310.5    4839  2309.8  4859.2 2307.23  4889.4 2305.38  4970.1 2302.93
  4980.2 2301.66  4990.3 2299.59  4997.7 2296.41  5002.8 2296.41  5005.5 2294.28
    5006 2293.78  5015.3 2293.78  5015.8 2294.28  5031.3 2296.15  5051.9 2300.94
  5059.9 2303.66  5065.1 2303.24  5072.6 2305.74  5082.9  2306.4  5093.2 2308.16
    5101 2313.08  5106.2 2315.56  5113.8 2317.05  5121.6 2320.12  5124.1 2320.12
#Mann= 3 ,-1 , 0
  4768.4     .07       0  5005.5     .07       0  5015.8     .07       0
Bank Sta=5005.5,5015.8
XS Rating Curve= 0 ,0
Exp/Cntr=0.3,0.1

Type RM Length L Ch R = 1 ,26448   ,218,218,218
BEGIN DESCRIPTION:
Long Branch 4239
END DESCRIPTION:
XS GIS Cut Line= 3
      1357233.41      6844230.78      1357315.01      6843887.96
      1357216.67      6843742.11
#Sta/Elev= 30
  4647.6 2311.56  4681.3 2309.71  4732.7 2308.34  4753.2    2307  4794.4 2307.11
  4849.8 2305.26  4886.9 2301.73    4892 2302.38  4897.2 2300.67  4917.7 2297.59
    4928 2298.06  4939.3 2296.73  4958.8 2296.88  4984.5 2292.84    4985 2292.34
  4994.3 2292.34  4994.8 2292.84    5003 2293.17  5007.5 2294.98  5013.5 2294.66
  5028.5 2297.38  5036.1 2301.63  5058.4 2305.35  5064.5 2305.62  5094.4 2313.68
  5100.4 2314.64  5108.5 2319.11  5115.4 2322.07  5151.4 2325.16  5175.9 2326.03
#Mann= 3 ,-1 , 0
  4647.6     .07       0  4984.5     .07       0  4994.8     .07       0
Bank Sta=4984.5,4994.8
XS Rating Curve= 0 ,0
Exp/Cntr=0.3,0.1

Type RM Length L Ch R = 1 ,26230   ,179,179,179
BEGIN DESCRIPTION:
Long Branch 4238
END DESCRIPTION:
XS GIS Cut Line= 3
      1357412.25      6844163.03      1357511.73      6843944.51
      1357478.21      6843765.52
#Sta/Elev= 30
  4759.9 2310.17  4774.8 2308.69  4864.3 2303.36  4886.3 2301.53  4895.5 2299.87
    4901 2299.81  4908.3 2297.25  4930.2 2293.15  4947.1 2291.41  4970.2 2293.07
  4985.2  2293.1    5000 2291.38  5000.3 2290.35  5000.8 2289.85  5010.1 2289.85
  5010.6 2290.35    5027 2292.65  5037.1 2296.02  5057.5 2296.95  5063.2 2298.01
  5068.2  2297.6  5077.8 2298.15    5088 2301.33  5108.4  2309.5  5115.8 2314.68
  5120.8  2314.4  5128.7 2318.64  5138.9 2321.49  5159.2 2323.84  5182.1 2325.62
#Mann= 3 ,-1 , 0
  4759.9     .07       0  5000.3     .07       0  5010.6     .07       0
Bank Sta=5000.3,5010.6
XS Rating Curve= 0 ,0
Exp/Cntr=0.3,0.1

Type RM Length L Ch R = 1 ,26051   ,285,285,285
BEGIN DESCRIPTION:
Long Branch 49.0
END DESCRIPTION:
XS GIS Cut Line= 3
        1357655.        6844188.      1357653.35       6844034.9
      1357540.72      6843788.09
#Sta/Elev= 30
  4846.9 2321.13  4866.9 2317.46  4876.9 2314.19  4886.9 2309.63  4896.9 2303.63
  4906.9  2299.5  4956.9  2294.5  4966.9 2292.52  4973.4 2289.08  4976.9 2287.22
  4999.9 2286.19  5000.4 2285.69  5010.3 2286.19  5010.6 2287.14  5033.6 2288.68
  5051.2 2291.82  5056.7 2291.77  5062.6 2293.99  5079.7 2296.76  5085.2 2296.44
  5102.7 2297.96  5117.5 2298.11  5161.5 2303.18  5171.8 2303.22  5194.5 2305.47
  5223.4 2309.92  5228.9 2311.59  5246.4 2313.42  5251.9 2315.11  5271.3 2316.74
#Mann= 4 ,-1 , 0
  4846.9    .035       0  4973.4     .07       0  4999.9     .07       0
  5010.3     .07       0
Bank Sta=4999.9,5010.3
XS Rating Curve= 0 ,0
Exp/Cntr=0.3,0.1

Type RM Length L Ch R = 1 ,25766   ,499,499,499
BEGIN DESCRIPTION:
Long Branch 48.0
END DESCRIPTION:
XS GIS Cut Line= 3
        1357855.        6843988.      1357824.71      6843817.88
      1357454.96      6843687.98
#Sta/Elev= 30
  4827.2 2310.15  4864.9 2303.97  4898.3 2298.32  4913.1 2288.18  4959.2  2286.5
  4984.5 2281.18    4985 2280.68  4994.9 2281.18  5015.2 2281.89  5020.9 2286.15
  5031.5 2289.64  5045.8 2289.15  5063.3  2291.5  5077.1  2290.3    5095  2291.8
  5116.3 2291.73  5170.1 2296.76  5190.5  2301.1  5195.8 2300.25  5201.1 2303.06
  5221.4 2307.75  5226.7 2306.35  5232.9 2309.16  5252.4 2313.26  5257.7 2312.48
  5283.4 2318.93  5288.7 2317.64  5345.4 2326.64  5350.7  2325.5  5391.9 2328.86
#Mann= 6 ,-1 , 0
  4827.2    .035       0  4864.9     .07       0  4984.5     .07       0
  4994.9     .07       0  5045.8     .16       0    5095     .07       0
Bank Sta=4984.5,4994.9
XS Rating Curve= 0 ,0
Exp/Cntr=0.3,0.1

Type RM Length L Ch R = 1 ,25267   ,498,498,498
BEGIN DESCRIPTION:
Long Branch 47.0
END DESCRIPTION:
XS GIS Cut Line= 3
        1358205.      6844037.98      1358203.86      6843528.58
        1358105.        6843288.
#Sta/Elev= 30
  4490.6 2324.96  4540.6 2319.72  4580.6 2310.42  4590.6 2308.98  4600.6 2306.08
  4620.6 2303.08  4670.6 2298.35  4720.6 2295.19  4790.6 2292.27  4920.6 2289.73
  4940.6 2281.74  4950.6 2280.53  4960.6 2281.27  5015.5  2279.9    5016  2279.4
  5029.1  2279.9  5095.6 2280.18  5120.2 2280.54  5130.4 2281.94  5144.1 2285.96
    5152 2287.19  5162.7 2287.37  5173.6 2289.86  5184.4 2295.12  5192.1 2300.51
    5216  2313.3  5221.4 2316.71  5227.7 2322.96  5238.5 2325.21  5260.1  2327.3
#Mann= 4 ,-1 , 0
  4490.6     .07       0  5015.5     .07       0  5029.1     .07       0
  5095.6     .07       0
Bank Sta=5015.5,5029.1
XS Rating Curve= 0 ,0
Exp/Cntr=0.3,0.1

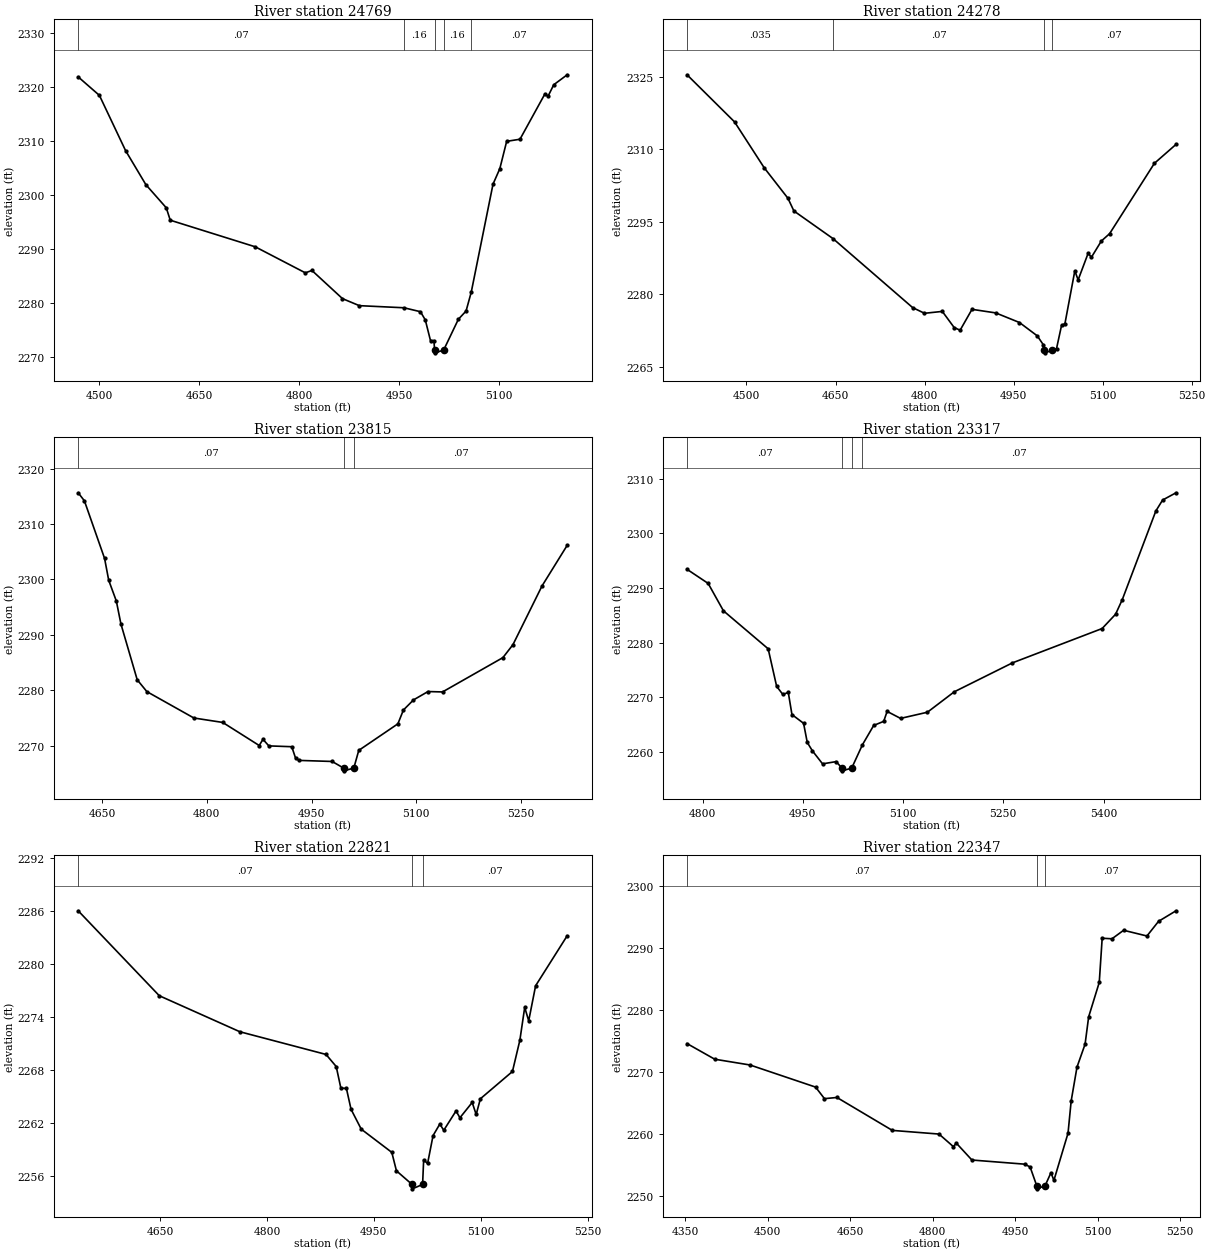
Type RM Length L Ch R = 1 ,24769   ,491,491,491
BEGIN DESCRIPTION:
Long Branch 46.0
END DESCRIPTION:
XS GIS Cut Line= 3
        1358305.      6843987.99      1358486.73      6843488.21
        1358455.      6843288.01
#Sta/Elev= 30
  4468.2 2321.84  4500.1 2318.41  4539.4 2308.18  4569.9 2301.87  4600.5 2297.59
  4606.5 2295.29  4734.2 2290.36  4809.4 2285.54  4819.3 2285.98  4865.2 2280.76
  4890.5 2279.46  4957.5 2279.07  4982.3 2278.34  4989.6 2276.81  4997.4 2272.98
  5002.6 2272.98  5003.5 2271.22    5004 2270.72  5017.1 2271.22  5039.3 2276.95
  5050.8 2278.46  5058.6 2281.96  5091.3 2301.97  5101.5 2304.83  5111.8  2309.9
  5131.8 2310.29    5169 2318.63  5174.1 2318.29  5182.5 2320.38  5202.7 2322.23
#Mann= 5 ,-1 , 0
  4468.2     .07       0  4957.5     .16       0  5003.5     .07       0
  5017.1     .16       0  5058.6     .07       0
Bank Sta=5003.5,5017.1
XS Rating Curve= 0 ,0
Exp/Cntr=0.3,0.1

Type RM Length L Ch R = 1 ,24278   ,463,463,463
BEGIN DESCRIPTION:
Long Branch 45.0
END DESCRIPTION:
XS GIS Cut Line= 3
        1358905.        6844238.       1358905.1       6843637.9
      1358804.98      6843437.97
#Sta/Elev= 30
  4399.9 2325.38  4479.9 2315.64  4529.9 2306.14  4569.9 2299.83  4579.9 2297.21
  4645.8 2291.49  4779.9 2277.22  4799.9 2276.04  4829.9 2276.43  4849.9 2273.09
  4859.9 2272.54  4879.9 2276.86  4919.9 2276.12  4959.9 2274.13  4989.9 2271.37
    5000 2269.54  5001.6 2268.36  5002.1 2267.86  5015.2 2268.36  5022.3 2268.74
  5030.8 2273.56  5036.4 2273.86  5053.1 2284.82  5058.7 2282.95  5075.5 2288.44
  5081.1 2287.64  5097.8 2290.99  5111.7 2292.51  5187.2 2307.07  5223.6 2310.98
#Mann= 4 ,-1 , 0
  4399.9    .035       0  4645.8     .07       0  5001.6     .07       0
  5015.2     .07       0
Bank Sta=5001.6,5015.2
XS Rating Curve= 0 ,0
Exp/Cntr=0.3,0.1

Type RM Length L Ch R = 1 ,23815   ,498,498,498
BEGIN DESCRIPTION:
Long Branch 44.0
END DESCRIPTION:
XS GIS Cut Line= 3
      1359654.99        6843838.      1359303.28      6843683.86
      1359104.97      6843437.96
#Sta/Elev= 30
    4616 2315.64  4624.9 2314.19  4653.8 2303.79  4659.7 2299.86  4670.6 2296.12
  4677.2 2291.97  4700.5 2281.91  4714.3 2279.78  4781.6 2275.02  4822.9 2274.22
  4875.1 2270.06  4880.5 2271.17  4888.9 2269.99  4921.7 2269.84  4927.3 2267.72
  4932.7 2267.37  4979.5 2267.18  4995.9 2265.99  4996.4 2265.49  5010.5 2265.99
  5017.6 2269.18  5073.6 2273.97  5081.5 2276.46  5095.9 2278.28  5116.7 2279.79
  5137.5 2279.72  5223.9 2285.91  5238.3 2288.25  5279.9 2298.84  5315.9 2306.16
#Mann= 3 ,-1 , 0
    4616     .07       0  4995.9     .07       0  5010.5     .07       0
Bank Sta=4995.9,5010.5
XS Rating Curve= 0 ,0
Exp/Cntr=0.3,0.1

Type RM Length L Ch R = 1 ,23317   ,496,496,496
BEGIN DESCRIPTION:
Long Branch 43.0
END DESCRIPTION:
XS GIS Cut Line= 3
      1359705.02      6843538.04      1359610.81      6843335.69
      1359105.01        6843388.
#Sta/Elev= 30
  4776.8  2293.4  4808.4 2290.82  4831.3  2285.8  4898.2 2278.85  4910.9 2271.97
  4920.2 2270.49  4928.3 2270.87  4933.8 2266.81  4951.2 2265.21  4956.7 2261.71
  4964.4 2260.17  4979.6 2257.79    5000  2258.2  5008.5 2257.01    5009 2256.51
  5023.2 2257.01  5039.3 2261.29  5056.1 2264.82  5071.1 2265.57  5076.2 2267.39
  5096.3 2266.11  5136.5 2267.24  5176.7 2270.98  5263.8 2276.28  5397.9 2282.56
    5418 2285.17  5428.1 2287.86  5478.3 2304.08  5488.4 2306.08  5508.5 2307.41
#Mann= 4 ,-1 , 0
  4776.8     .07       0  5008.5     .07       0  5023.2     .07       0
  5039.3     .07       0
Bank Sta=5008.5,5023.2
XS Rating Curve= 0 ,0
Exp/Cntr=0.3,0.1

Type RM Length L Ch R = 1 ,22821   ,474,474,474
BEGIN DESCRIPTION:
Long Branch 42.0
END DESCRIPTION:
XS GIS Cut Line= 3
      1359955.02      6843238.02      1359654.91      6842882.96
      1359455.01      6842788.01
#Sta/Elev= 30
  4535.1 2286.01  4648.9 2276.39    4762 2272.31  4882.9 2269.74  4897.2 2268.37
  4903.7 2265.93  4911.5 2265.89    4918 2263.53  4932.3 2261.28  4975.2 2258.65
  4981.7 2256.56  5003.6 2255.02  5004.1 2254.52  5018.4 2255.02  5019.9 2257.81
  5025.4 2257.39  5033.1 2260.55  5042.6 2261.86  5048.1 2261.15  5065.3 2263.34
  5070.8 2262.57    5088  2264.3  5093.6 2262.94  5099.5 2264.72  5144.5 2267.81
  5154.9 2271.35  5161.7 2275.07  5167.3 2273.55    5177 2277.52  5221.3 2283.18
#Mann= 3 ,-1 , 0
  4535.1     .07       0  5003.6     .07       0  5018.4     .07       0
Bank Sta=5003.6,5018.4
XS Rating Curve= 0 ,0
Exp/Cntr=0.3,0.1

Type RM Length L Ch R = 1 ,22347   ,481,481,481
BEGIN DESCRIPTION:
Long Branch 41.0
END DESCRIPTION:
XS GIS Cut Line= 3
      1360005.01      6843088.03       1359824.9      6842467.03
      1359904.99      6842238.03
#Sta/Elev= 30
  4353.4 2274.57  4403.8 2272.05    4468 2271.12  4587.2 2267.56  4603.3  2265.7
    4626 2265.89  4726.7 2260.59  4811.6    2260  4837.8 2257.97    4843 2258.55
  4871.4 2255.82  4967.7 2255.15  4977.3 2254.69  4989.3 2251.68  4989.8 2251.18
  5004.5 2251.68  5015.2 2253.78  5020.5 2252.54  5046.2 2260.14  5051.9 2265.32
  5062.5 2270.78  5077.2 2274.47  5083.7 2278.87    5103 2284.42  5108.3 2291.53
  5126.1 2291.44  5147.3 2292.81  5189.7 2291.89  5210.8 2294.25  5242.6 2295.95
#Mann= 3 ,-1 , 0
  4353.4     .07       0  4989.3     .07       0  5004.5     .07       0
Bank Sta=4989.3,5004.5
XS Rating Curve= 0 ,0
Exp/Cntr=0.3,0.1

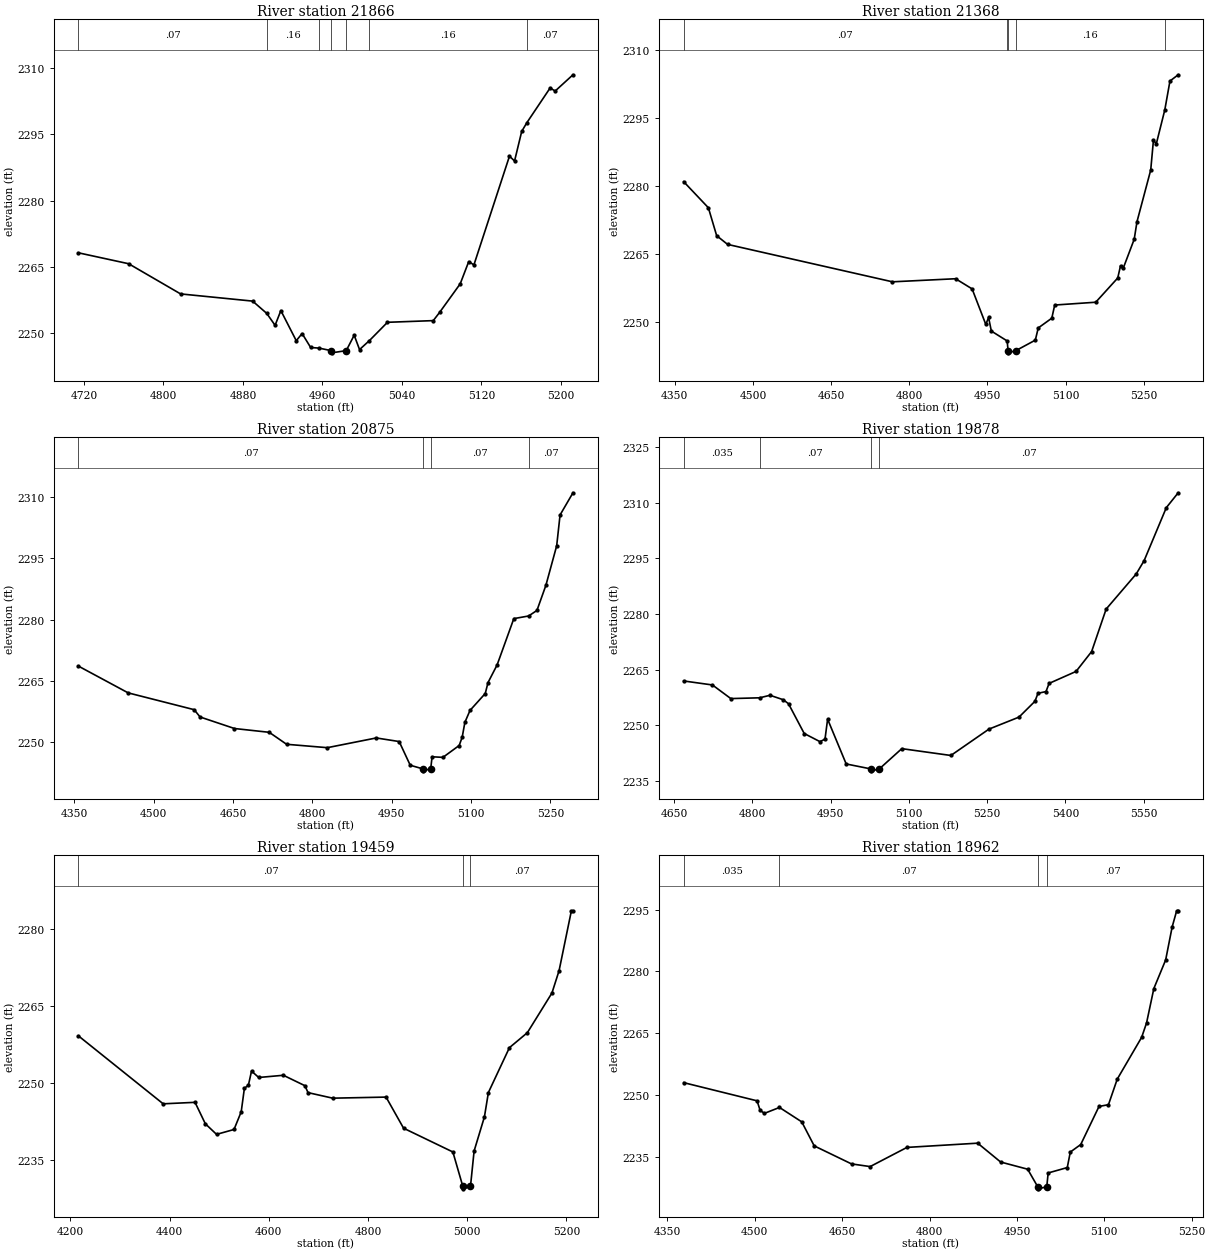
Type RM Length L Ch R = 1 ,21866   ,498,498,498
BEGIN DESCRIPTION:
Long Branch 40.0
END DESCRIPTION:
XS GIS Cut Line= 3
      1360104.99      6842738.01      1360252.69      6842493.68
      1360304.99      6842288.03
#Sta/Elev= 30
  4714.5 2268.17    4765  2265.7  4817.3 2258.86  4889.8 2257.23    4904 2254.45
  4912.4 2251.74  4918.2 2255.08  4933.7 2248.26  4939.6 2249.88  4948.2 2246.72
  4956.7 2246.58  4968.8 2246.01  4969.3 2245.51    4984 2246.01    4992  2249.5
  4997.4 2246.25  5007.4  2248.3  5025.5 2252.43  5071.6 2252.81  5078.1 2254.71
  5098.7 2261.14  5107.3 2266.19  5112.5 2265.43  5148.3 2290.08  5153.4 2288.97
  5160.6 2295.68  5165.8 2297.66  5189.2 2305.52  5194.3 2304.83  5212.2 2308.51
#Mann= 7 ,-1 , 0
  4714.5     .07       0    4904     .16       0  4956.7     .07       0
  4968.8     .07       0    4984     .07       0  5007.4     .16       0
  5165.8     .07       0
Bank Sta=4968.8,4984
XS Rating Curve= 0 ,0
Exp/Cntr=0.3,0.1

Type RM Length L Ch R = 1 ,21368   ,493,493,493
BEGIN DESCRIPTION:
Long Branch 39.0
END DESCRIPTION:
XS GIS Cut Line= 3
        1360455.      6843288.01      1360655.15       6842687.7
        1360555.      6842387.99
#Sta/Elev= 30
  4367.2 2280.87  4414.6 2275.12  4430.5 2268.96  4451.5 2267.04  4767.8 2258.79
  4888.9 2259.47  4920.6 2257.23  4946.9 2249.39  4952.2 2250.93  4957.5 2247.93
  4987.9 2245.75  4989.6 2243.63  4990.1 2243.13  5004.8 2243.63  5041.9 2245.93
  5047.5 2248.62  5073.5 2250.77  5079.1 2253.67  5157.8 2254.29    5200 2259.63
  5205.4 2262.35  5210.7 2261.83  5231.6 2268.17    5237 2272.07  5263.3 2283.44
  5268.6  2290.1  5273.9 2289.16  5290.3 2296.69  5300.2 2303.06    5316 2304.44
#Mann= 5 ,-1 , 0
  4367.2     .07       0  4987.9     .16       0  4989.6     .07       0
  5004.8     .16       0  5290.3     .07       0
Bank Sta=4989.6,5004.8
XS Rating Curve= 0 ,0
Exp/Cntr=0.3,0.1

Type RM Length L Ch R = 1 ,20875   ,997,997,997
BEGIN DESCRIPTION:
Long Branch 38.0
END DESCRIPTION:
XS GIS Cut Line= 3
      1360905.01      6843287.97      1361091.93      6842673.89
      1361155.01      6842387.96
#Sta/Elev= 30
  4358.1 2268.59  4452.1 2262.04  4576.8 2257.93    4588 2256.14    4653 2253.32
  4718.7 2252.39  4751.5 2249.46  4828.5 2248.63    4921 2251.01  4964.3 2250.13
  4985.2 2244.33  5008.6 2243.46  5009.1 2242.96  5023.9 2243.46  5026.5  2246.4
    5047 2246.26  5077.7 2249.16  5083.4 2251.19  5088.5 2254.83  5098.2 2257.75
    5127 2261.89  5132.2 2264.56  5149.4 2268.88    5181 2280.22  5208.9 2280.86
  5224.7 2282.22  5241.6 2288.36    5262 2298.04  5268.4 2305.59  5292.8 2311.02
#Mann= 4 ,-1 , 0
  4358.1     .07       0  5008.6     .07       0  5023.9     .07       0
  5208.9     .07       0
Bank Sta=5008.6,5023.9
XS Rating Curve= 0 ,0
Exp/Cntr=0.3,0.1

Type RM Length L Ch R = 1 ,19878   ,419,419,419
BEGIN DESCRIPTION:
Long Branch 37.0
END DESCRIPTION:
XS GIS Cut Line= 3
        1361605.      6843137.97      1361635.08      6842808.03
      1361305.02      6842288.04
#Sta/Elev= 30
  4668.7    2262  4723.8 2260.92    4759 2257.25  4814.2 2257.46  4834.1 2258.14
  4859.5 2256.94  4869.5 2255.86  4899.6 2247.84  4929.7 2245.65  4939.4 2246.32
  4944.4  2251.7    4980 2239.63  5027.9 2238.28  5028.4 2237.78  5043.3 2238.28
  5086.5 2243.76  5180.5 2241.92  5253.4 2249.02    5311 2252.26  5341.5 2256.52
  5347.4 2258.68  5362.7 2259.14  5368.6 2261.34  5420.3 2264.57  5450.1 2269.92
  5477.9 2281.37  5535.5 2290.83  5550.7 2294.44  5593.1 2308.69  5615.9 2312.71
#Mann= 4 ,-1 , 0
  4668.7    .035       0  4814.2     .07       0  5027.9     .07       0
  5043.3     .07       0
Bank Sta=5027.9,5043.3
XS Rating Curve= 0 ,0
Exp/Cntr=0.3,0.1

Type RM Length L Ch R = 1 ,19459   ,497,497,497
BEGIN DESCRIPTION:
Long Branch 36.0
END DESCRIPTION:
XS GIS Cut Line= 3
      1362204.98      6843037.97      1361721.43      6842421.23
      1361554.99      6842287.99
#Sta/Elev= 30
  4216.3 2259.27  4387.1 2246.04  4451.3 2246.33  4472.1 2242.15  4494.7 2240.09
  4529.9 2241.04  4544.4 2244.49  4550.8 2249.06  4558.9 2249.67  4565.2 2252.42
  4579.7 2251.17  4629.4  2251.6  4672.8 2249.57  4679.1 2248.22  4728.8 2247.14
  4836.4 2247.35  4871.7 2241.29  4971.1 2236.66  4991.1 2229.98  4991.6 2229.48
  5006.6 2229.98  5013.9 2236.85  5034.7  2243.5  5042.7 2248.24  5085.1 2256.98
  5121.2 2259.89  5170.8 2267.62  5185.2 2271.98    5210 2283.64  5213.2 2283.64
#Mann= 3 ,-1 , 0
  4216.3     .07       0  4991.1     .07       0  5006.6     .07       0
Bank Sta=4991.1,5006.6
XS Rating Curve= 0 ,0
Exp/Cntr=0.3,0.1

Type RM Length L Ch R = 1 ,18962   ,486,486,486
BEGIN DESCRIPTION:
Long Branch 35.0
END DESCRIPTION:
XS GIS Cut Line= 3
      1362355.02      6842788.05      1362138.44      6842204.86
      1362204.99      6841988.05
#Sta/Elev= 30
  4377.9 2252.96  4503.9 2248.54  4509.2  2246.2  4516.6  2245.5  4542.4 2246.93
  4580.6 2243.43    4602 2237.59    4666 2233.21    4698 2232.56  4761.2 2237.22
  4882.6 2238.25    4922 2233.67  4968.4 2231.92  4985.7 2227.65  4986.2 2227.15
  5001.2 2227.65  5003.6 2231.01  5036.4 2232.32  5041.6 2236.09  5059.5 2237.92
  5090.9 2247.18  5107.1  2247.6  5122.2 2253.82  5164.1 2263.98  5172.5 2267.47
    5185 2275.83  5205.3 2282.78  5216.4 2290.78  5224.2 2294.73  5226.8 2294.73
#Mann= 4 ,-1 , 0
  4377.9    .035       0  4542.4     .07       0  4985.7     .07       0
  5001.2     .07       0
Bank Sta=4985.7,5001.2
XS Rating Curve= 0 ,0
Exp/Cntr=0.3,0.1

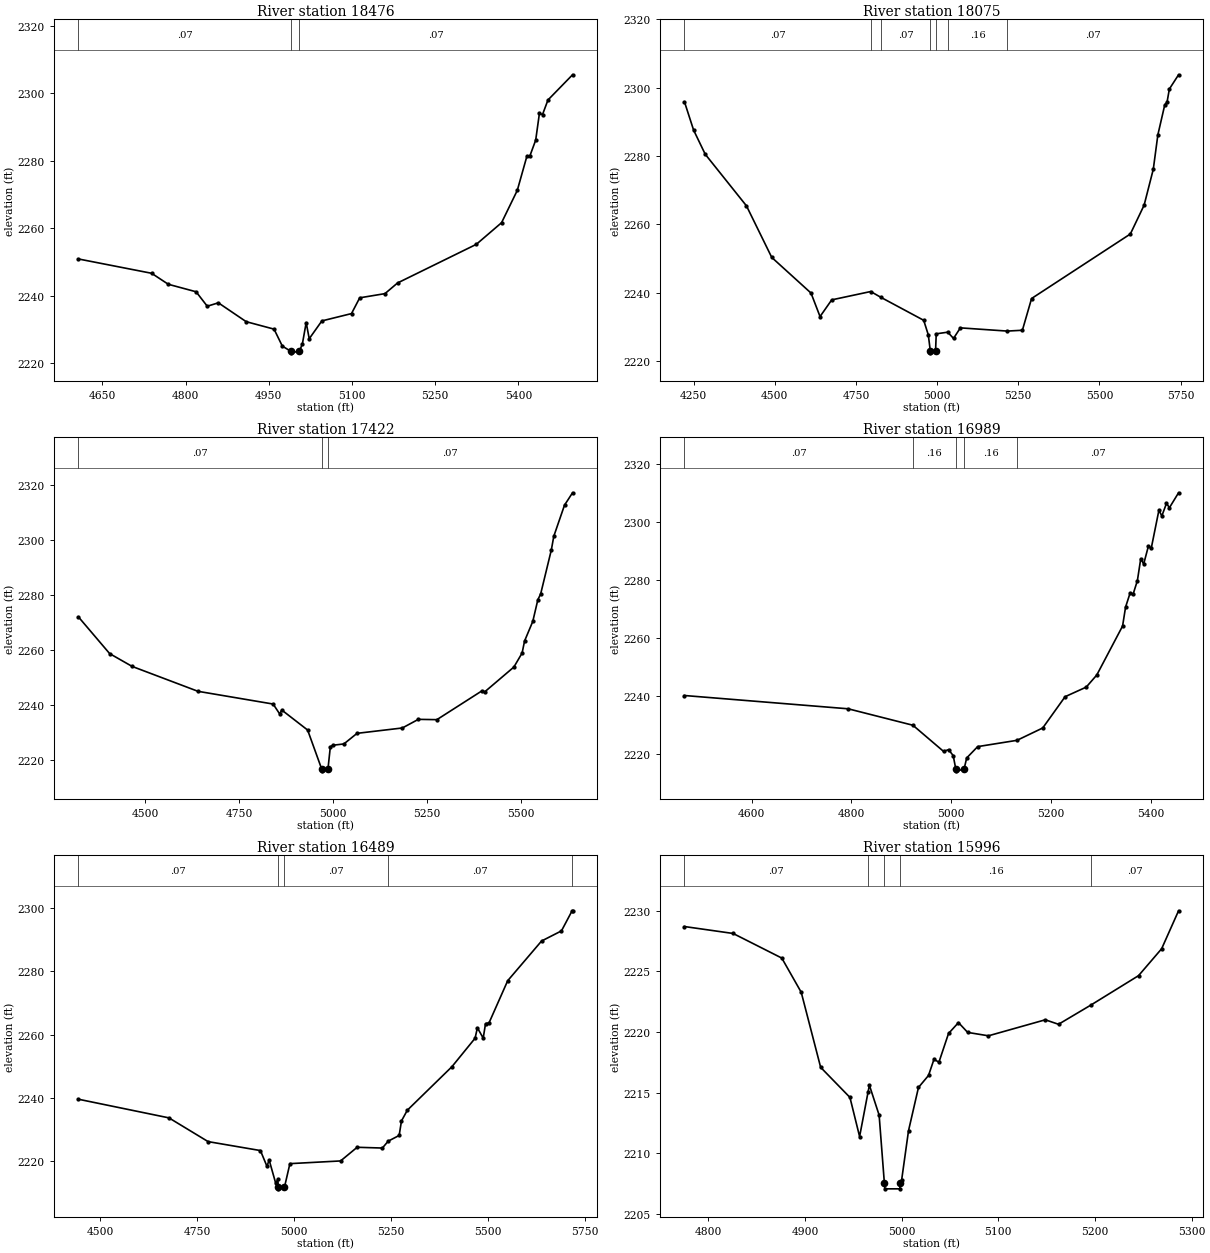
Type RM Length L Ch R = 1 ,18476   ,401,401,401
BEGIN DESCRIPTION:
Long Branch 34.0
END DESCRIPTION:
XS GIS Cut Line= 3
      1362548.84      6842779.46      1362517.98      6842387.58
      1362304.99      6841937.97
#Sta/Elev= 30
  4606.9 2250.96  4738.8 2246.72  4768.9 2243.46    4819 2241.24  4839.1 2236.96
  4859.1 2237.97  4909.3 2232.38  4959.5 2230.17  4974.4 2225.15  4989.3 2223.65
  4989.8 2223.15  5005.3 2223.65  5010.6 2225.83  5017.4 2232.11  5022.9 2227.33
  5045.7 2232.61  5099.1 2234.78  5113.9 2239.45  5159.4 2240.69  5182.1 2243.85
  5324.1  2255.3  5369.6 2261.71  5397.9 2271.27  5415.1 2281.32  5420.6 2281.48
  5431.1 2286.17  5437.8 2294.09  5443.4 2293.74  5453.2 2298.06  5497.5 2305.53
#Mann= 3 ,-1 , 0
  4606.9     .07       0  4989.3     .07       0  5005.3     .07       0
Bank Sta=4989.3,5005.3
XS Rating Curve= 0 ,0
Exp/Cntr=0.3,0.1

Type RM Length L Ch R = 1 ,18075   ,653,653,653
BEGIN DESCRIPTION:
Long Branch 33.0
END DESCRIPTION:
XS GIS Cut Line= 3
      1363455.02      6842988.02       1362876.1      6842468.41
      1362354.98      6841937.98
#Sta/Elev= 30
  4222.1 2295.85  4250.2 2287.59    4286 2280.53  4413.1 2265.43  4490.9 2250.37
  4611.8 2239.95  4639.6 2233.08  4675.5 2237.96  4795.6  2240.4    4827  2238.7
  4958.8 2231.99    4973 2227.72  4979.2 2222.98  4979.7 2222.48  4995.3 2222.98
  4997.4 2228.04    5033 2228.52  5050.6 2226.69  5071.7 2229.78    5216 2228.84
  5262.7 2229.08    5291 2238.36  5595.1 2257.21  5637.5 2265.63  5665.8 2276.15
  5679.9 2286.22  5701.2    2295  5708.2 2295.77  5715.3  2299.6  5743.6 2303.75
#Mann= 7 ,-1 , 0
  4222.1     .07       0  4795.6    .035       0    4827     .07       0
  4979.2     .07       0  4995.3     .07       0    5033     .16       0
    5216     .07       0
Bank Sta=4979.2,4995.3
XS Rating Curve= 0 ,0
Exp/Cntr=0.3,0.1

Type RM Length L Ch R = 1 ,17422   ,433,433,433
BEGIN DESCRIPTION:
Long Branch 32.0
END DESCRIPTION:
XS GIS Cut Line= 3
      1363505.02      6842838.04       1363221.8      6842221.58
      1362805.01      6841738.01
#Sta/Elev= 30
  4321.6 2271.97  4404.8 2258.64  4464.7 2253.99  4640.1 2244.95  4840.5 2240.32
    4858 2236.71  4863.5 2238.15  4932.4 2230.88  4970.3 2216.56  4970.8 2216.06
  4986.5 2216.56  4992.9 2224.78  4999.2 2225.35    5029 2225.83  5064.1 2229.68
  5184.8 2231.63  5227.5 2234.76  5276.9 2234.65  5397.6 2245.17  5404.2 2244.73
  5482.1 2253.76    5504 2258.85  5510.6 2263.23  5532.5 2270.35    5546 2278.24
  5553.4 2280.28  5581.9  2296.3  5588.5 2301.28    5617 2312.56  5638.4 2317.06
#Mann= 3 ,-1 , 0
  4321.6     .07       0  4970.3     .07       0  4986.5     .07       0
Bank Sta=4970.3,4986.5
XS Rating Curve= 0 ,0
Exp/Cntr=0.3,0.1

Type RM Length L Ch R = 1 ,16989   ,500,500,500
BEGIN DESCRIPTION:
Long Branch 31.0
END DESCRIPTION:
XS GIS Cut Line= 3
      1363511.89      6842404.22      1363454.35      6841872.72
      1363209.68       6841488.4
#Sta/Elev= 30
  4465.4 2240.19  4793.5 2235.61  4923.2 2229.94  4984.6 2220.93  4994.7 2221.53
    5004 2219.46  5009.3 2214.72  5009.8 2214.22  5025.6 2214.72    5031 2218.66
    5053 2222.57  5131.8 2224.74  5183.4    2229  5228.2 2239.78  5270.6 2243.09
  5291.7 2247.26  5343.4 2264.14  5349.4 2270.67  5358.6 2275.59  5364.5 2275.12
  5373.1 2279.81  5379.8 2287.37  5385.7 2285.53    5395  2291.6  5400.9 2290.99
  5416.2 2304.06  5422.1  2302.1  5431.4 2306.45  5437.3 2304.95  5455.6 2310.09
#Mann= 5 ,-1 , 0
  4465.4     .07       0  4923.2     .16       0  5009.3     .07       0
  5025.6     .16       0  5131.8     .07       0
Bank Sta=5009.3,5025.6
XS Rating Curve= 0 ,0
Exp/Cntr=0.3,0.1

Type RM Length L Ch R = 1 ,16489   ,493,493,493
BEGIN DESCRIPTION:
Long Branch 30.0
END DESCRIPTION:
XS GIS Cut Line= 3
      1363554.99      6842388.01      1363799.84      6841888.38
      1363404.99      6841287.98
#Sta/Elev= 30
  4443.6 2239.47  4677.1 2233.56  4778.2 2226.03  4913.2 2223.19  4930.1 2218.19
  4935.7  2220.2  4952.6 2212.85  4958.2 2214.08  4958.9 2211.55  4959.4 2211.05
  4975.2 2211.55  4989.3 2219.04  5120.1  2219.9  5162.8 2224.23  5227.9 2223.99
  5242.9 2226.17  5271.2 2227.98  5277.2 2232.59  5292.3 2235.99  5407.4 2249.79
  5467.1 2258.81  5473.1 2262.13  5488.1 2258.85  5494.1 2263.45  5503.1 2263.68
  5551.3 2277.06  5638.7 2289.65    5690 2292.86  5717.5 2299.24  5718.6 2299.24
#Mann= 5 ,-1 , 0
  4443.6     .07       0  4958.9     .07       0  4975.2     .07       0
  5242.9     .07       0  5717.5    .035       0
Bank Sta=4958.9,4975.2
XS Rating Curve= 0 ,0
Exp/Cntr=0.3,0.1

Type RM Length L Ch R = 1 ,15996   ,492,492,492
BEGIN DESCRIPTION:
Long Branch 29.0
END DESCRIPTION:
XS GIS Cut Line= 3
        1364155.      6842337.98       1364181.3      6842114.82
      1364255.01      6841837.97
#Sta/Elev= 30
  4775.3  2228.7  4825.6 2228.13    4876  2226.1  4896.1 2223.28  4916.2 2217.09
  4946.5 2214.61  4956.5 2211.38  4965.3 2215.07  4966.6 2215.62  4976.7 2213.15
  4982.1 2207.57  4982.6 2207.07  4998.1 2207.07  4998.6 2207.57    5000  2207.8
  5007.1 2211.86  5017.4 2215.43  5027.8 2216.42  5033.4 2217.74  5038.6 2217.52
  5048.5 2219.88  5058.8 2220.78  5068.3 2219.97  5089.8 2219.69  5148.6 2221.01
  5162.3 2220.64  5195.9 2222.23  5245.1 2224.65    5269 2226.87  5286.5    2230
#Mann= 5 ,-1 , 0
  4775.3     .07       0  4965.3     .16       0  4982.1     .07       0
  4998.6     .16       0  5195.9     .07       0
Bank Sta=4982.1,4998.6
XS Rating Curve= 0 ,0
Exp/Cntr=0.3,0.1

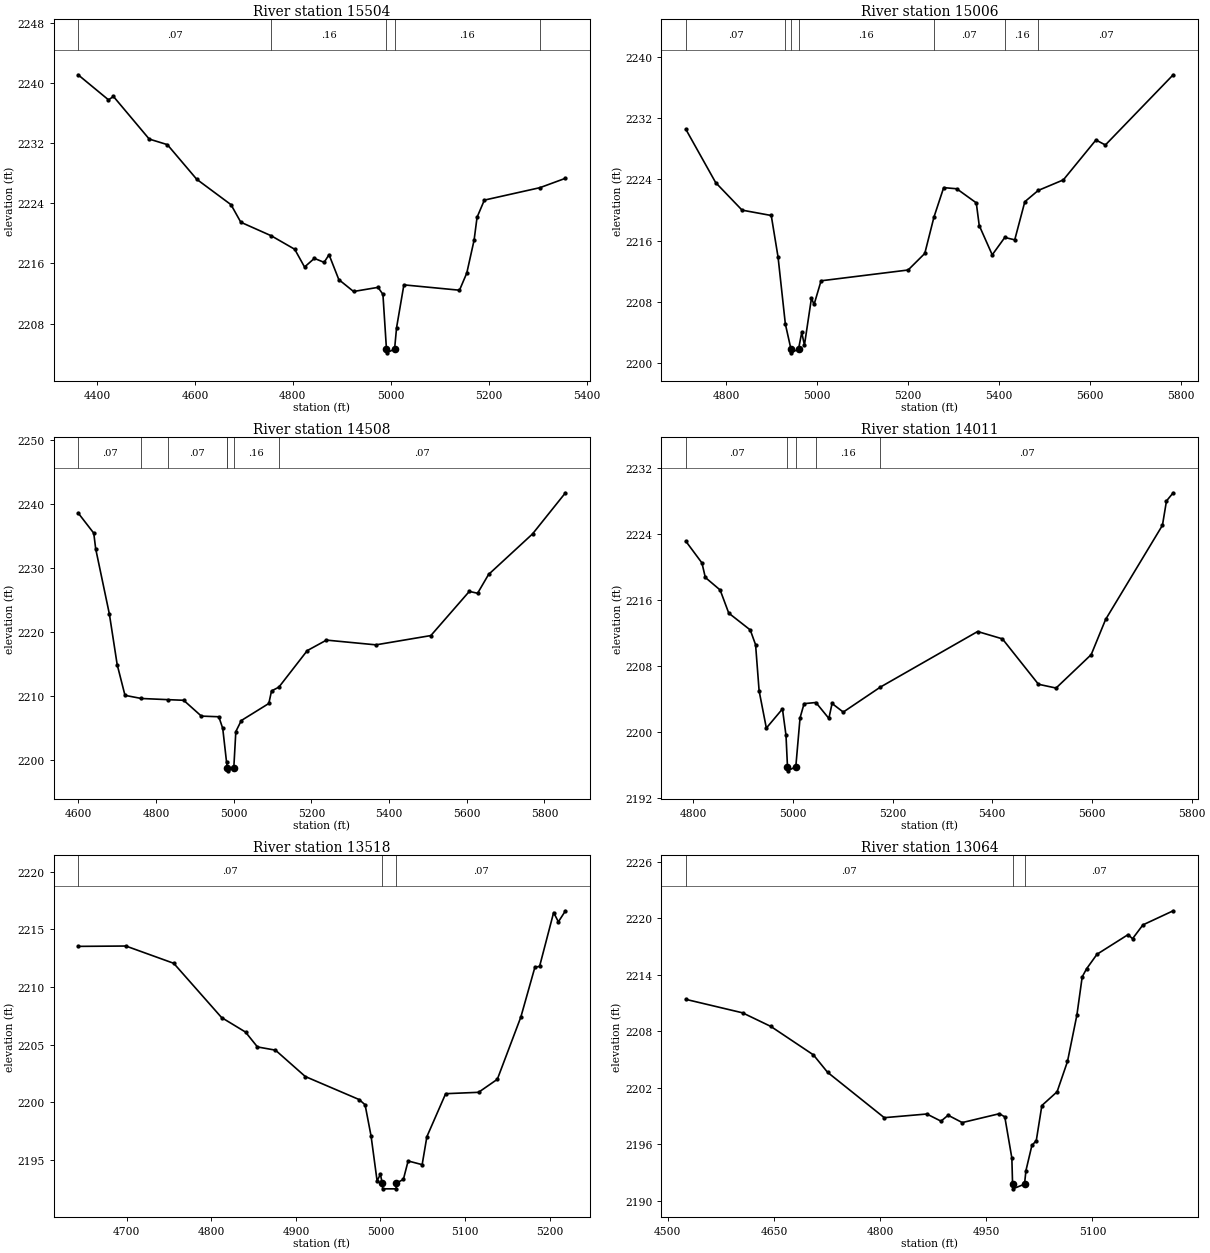
Type RM Length L Ch R = 1 ,15504   ,498,498,498
BEGIN DESCRIPTION:
Long Branch 28.0
END DESCRIPTION:
XS GIS Cut Line= 3
      1364636.58      6842820.08      1364607.29      6842182.15
        1364405.        6841888.
#Sta/Elev= 30
  4361.4 2241.06  4423.5 2237.73  4433.6 2238.18  4506.7 2232.52  4543.7 2231.78
  4603.7 2227.18  4673.8  2223.8  4693.8 2221.47    4756 2219.67  4803.9 2217.88
    4824 2215.52    4844 2216.67    4864 2216.14    4874 2217.16    4894 2213.85
  4924.1 2212.27  4974.1 2212.82  4984.1 2211.89  4991.3 2204.62  4991.8 2204.12
  5007.9 2204.62    5012 2207.48  5026.9 2213.15  5140.5 2212.44  5155.4 2214.72
  5170.3 2219.08  5176.4 2222.13  5191.3 2224.41  5304.7 2226.06    5357 2227.31
#Mann= 5 ,-1 , 0
  4361.4     .07       0    4756     .16       0  4991.3     .07       0
  5007.9     .16       0  5304.7     .07       0
Bank Sta=4991.3,5007.9
XS Rating Curve= 0 ,0
Exp/Cntr=0.3,0.1

Type RM Length L Ch R = 1 ,15006   ,498,498,498
BEGIN DESCRIPTION:
Long Branch 27.0
END DESCRIPTION:
XS GIS Cut Line= 3
      1365205.01      6842388.02       1365053.4      6842141.86
      1364554.99      6841537.98
#Sta/Elev= 30
  4710.9 2230.55  4776.6 2223.58  4834.6 2219.99  4898.8 2219.29  4913.8 2213.85
  4929.8 2205.12  4942.1 2201.85  4942.6 2201.35  4958.8 2201.85  4965.9 2204.01
  4971.8 2202.36  4987.2 2208.48    4993 2207.67  5008.4 2210.76  5199.9 2212.17
  5236.5 2214.33  5256.8  2219.1  5278.1 2222.93  5306.8 2222.78  5349.8 2220.94
  5356.3 2217.98  5384.9 2214.15  5412.5 2216.42  5434.4 2216.11  5456.6 2221.09
    5486 2222.56  5541.3 2223.94    5613 2229.15  5633.8  2228.5    5783 2237.67
#Mann= 7 ,-1 , 0
  4710.9     .07       0  4929.8     .16       0  4942.1     .07       0
  4958.8     .16       0  5256.8     .07       0  5412.5     .16       0
    5486     .07       0
Bank Sta=4942.1,4958.8
XS Rating Curve= 0 ,0
Exp/Cntr=0.3,0.1

Type RM Length L Ch R = 1 ,14508   ,497,497,497
BEGIN DESCRIPTION:
Long Branch 26.0
END DESCRIPTION:
XS GIS Cut Line= 3
        1365455.      6842338.01      1365410.89      6841940.15
      1364805.01      6841338.01
#Sta/Elev= 30
  4599.7 2238.63    4640 2235.47    4645 2233.02  4680.2 2222.85  4700.3 2214.95
  4720.4 2210.16  4762.5 2209.67  4830.4 2209.49  4871.4 2209.39    4917 2206.92
  4961.9 2206.82    4972    2205  4981.7  2199.8  4983.8 2198.88  4984.3 2198.38
  5000.5 2198.88  5005.7 2204.51  5019.8 2206.23  5090.6 2208.89  5097.6 2210.85
  5116.5 2211.44  5189.5 2217.14    5239 2218.78  5366.3 2218.04  5507.7 2219.49
  5606.7 2226.38    5628 2226.09  5656.2 2229.02  5769.4 2235.35  5854.2 2241.77
#Mann= 7 ,-1 , 0
  4599.7     .07       0  4762.5     .16       0  4830.4     .07       0
  4981.7     .16       0  4983.8     .07       0  5000.5     .16       0
  5116.5     .07       0
Bank Sta=4983.8,5000.5
XS Rating Curve= 0 ,0
Exp/Cntr=0.3,0.1

Type RM Length L Ch R = 1 ,14011   ,493,493,493
BEGIN DESCRIPTION:
Long Branch 25.0
END DESCRIPTION:
XS GIS Cut Line= 3
        1365955.      6842138.01       1365875.6      6841938.64
      1365405.03      6841338.03
#Sta/Elev= 30
  4785.4 2223.13  4817.7  2220.5  4824.5 2218.74  4854.2 2217.22  4871.5 2214.42
  4914.6 2212.38  4925.3 2210.59  4932.4    2205  4946.9 2200.49  4979.2 2202.81
  4986.3 2199.62  4989.3 2195.81  4989.8 2195.31    5006 2195.81  5014.5 2201.73
  5022.6 2203.45  5046.3 2203.59  5072.3 2201.66  5078.7 2203.47  5101.2 2202.43
  5175.7 2205.46  5370.7 2212.19  5420.4  2211.3  5492.7  2205.8    5528 2205.34
  5598.5 2209.39  5627.4 2213.65  5741.4 2225.06  5749.5 2228.01    5763    2229
#Mann= 5 ,-1 , 0
  4785.4     .07       0  4989.3     .07       0    5006     .07       0
  5046.3     .16       0  5175.7     .07       0
Bank Sta=4989.3,5006
XS Rating Curve= 0 ,0
Exp/Cntr=0.3,0.1

Type RM Length L Ch R = 1 ,13518   ,454,454,454
BEGIN DESCRIPTION:
Long Branch 24.0
END DESCRIPTION:
XS GIS Cut Line= 3
      1366105.01      6841738.01      1365854.52       6841482.8
      1365754.98      6841287.96
#Sta/Elev= 30
  4642.4 2213.52  4698.9 2213.55  4755.5 2212.05  4812.1 2207.34  4840.4 2206.08
  4854.5 2204.79  4875.8 2204.51  4911.1 2202.22  4974.8 2200.22  4981.8 2199.77
  4988.9 2197.05    4996 2193.16  4999.9 2193.73  5002.1 2192.97  5002.6 2192.47
  5018.4 2192.47  5018.9 2192.97  5027.1 2193.29  5032.7 2194.89  5049.3 2194.57
  5054.9    2197  5077.1 2200.73    5116 2200.85  5138.2 2201.98    5166 2207.38
  5182.6  2211.7  5188.2 2211.79  5204.8 2216.46  5210.4 2215.65  5218.8 2216.61
#Mann= 3 ,-1 , 0
  4642.4     .07       0  5002.1     .07       0  5018.9     .07       0
Bank Sta=5002.1,5018.9
XS Rating Curve= 0 ,0
Exp/Cntr=0.3,0.1

Type RM Length L Ch R = 1 ,13064   ,981,981,981
BEGIN DESCRIPTION:
Long Branch 23.0
END DESCRIPTION:
XS GIS Cut Line= 3
        1366105.      6841587.97      1366078.06      6841114.14
      1365905.04      6840988.03
#Sta/Elev= 30
  4525.4 2211.38  4605.5 2209.95  4645.6  2208.5  4705.7 2205.48  4725.7 2203.63
  4805.8 2198.81  4865.9  2199.2    4886 2198.44    4896 2199.07    4916 2198.29
  4968.4 2199.23  4976.1  2198.9  4986.1 2194.52  4987.1 2191.75  4987.6 2191.25
    5004 2191.75    5006 2193.19  5014.4 2195.86  5020.6 2196.37  5028.5  2200.1
    5050 2201.56  5064.7 2204.78    5078 2209.71  5085.5 2213.77  5091.7 2214.63
  5106.4 2216.17  5150.4 2218.26  5156.6 2217.82  5171.3 2219.29  5214.1 2220.79
#Mann= 3 ,-1 , 0
  4525.4     .07       0  4987.1     .07       0    5004     .07       0
Bank Sta=4987.1,5004
XS Rating Curve= 0 ,0
Exp/Cntr=0.3,0.1