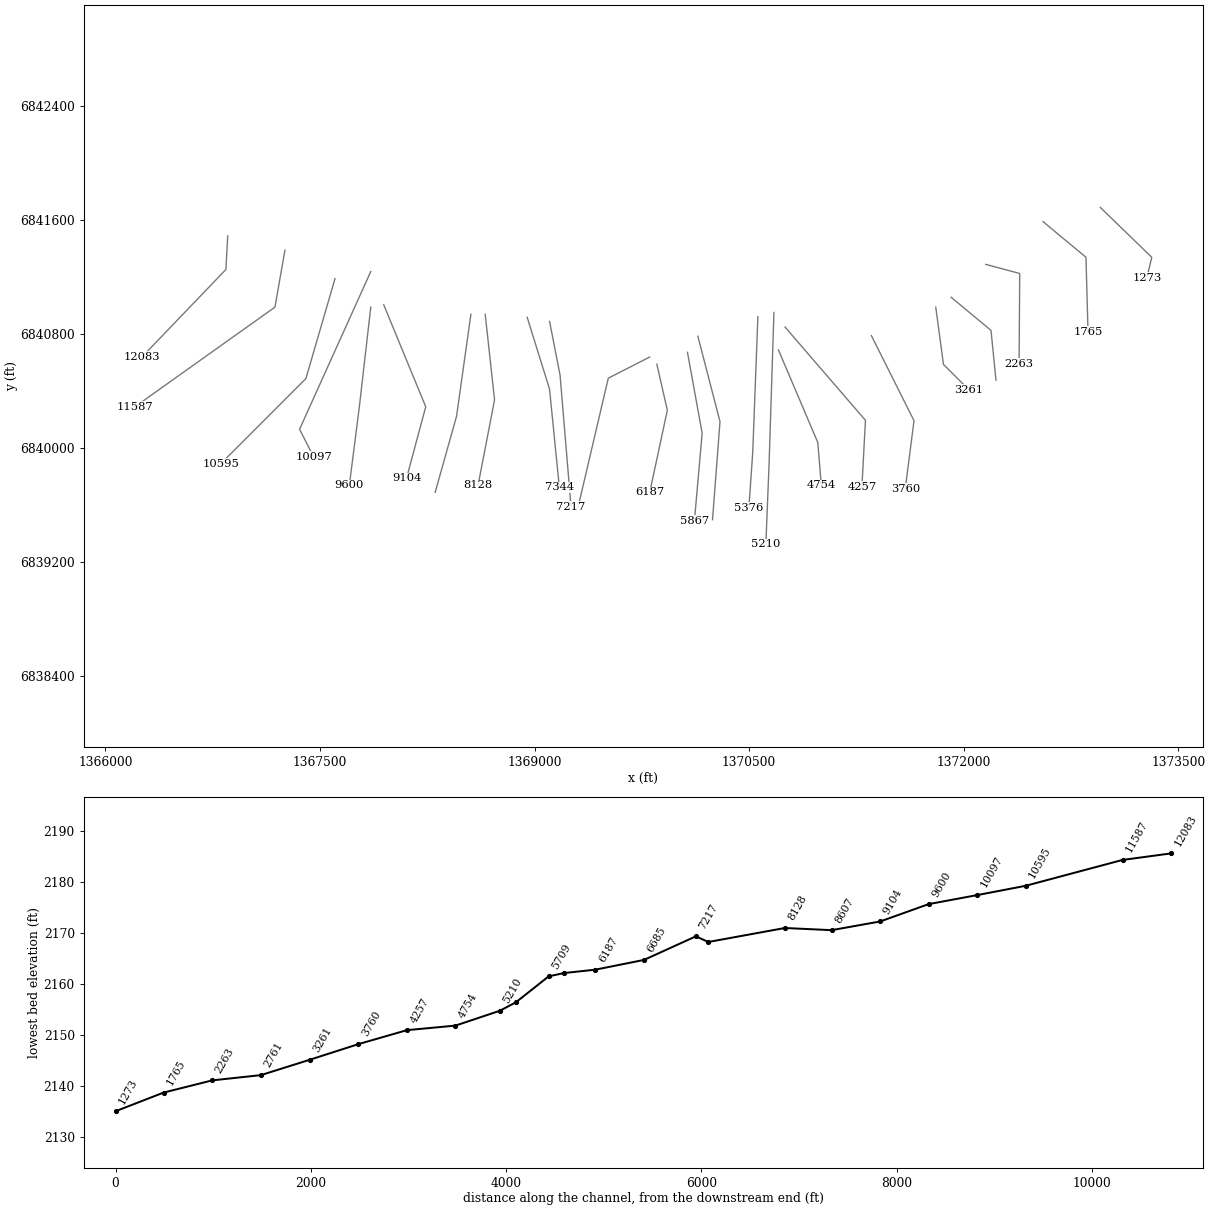
HEC-RAS study Long Branch.prj: Long Branch Base Level Engineering

--- Long Branch.g01 (geometry) --- (continued)

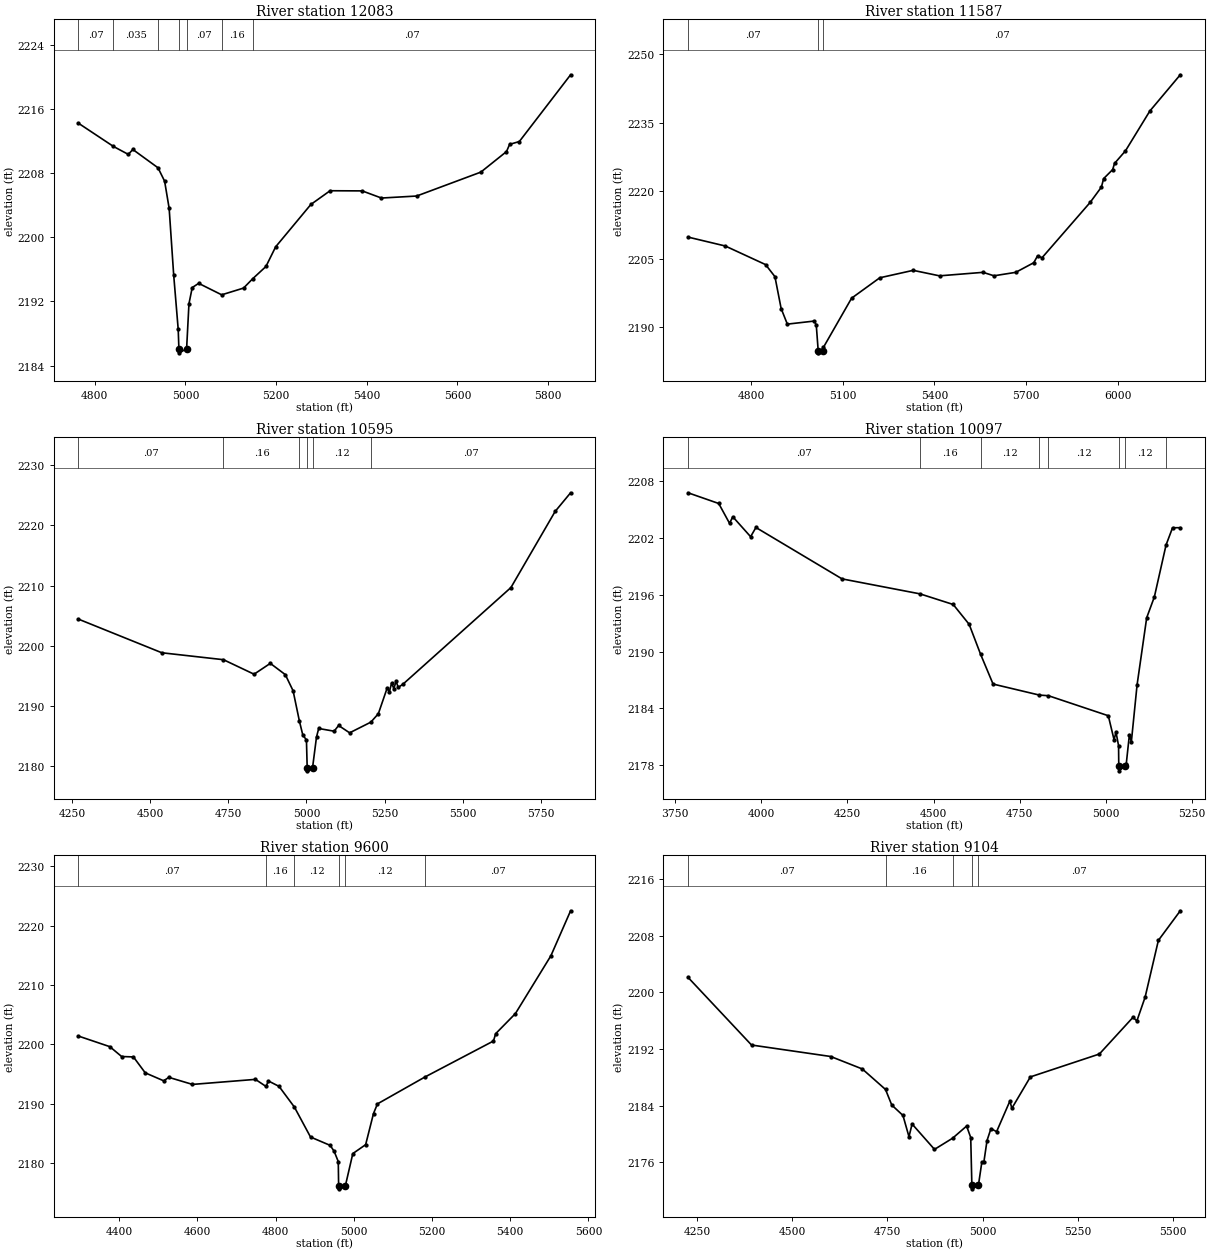
Type RM Length L Ch R = 1 ,12083   ,496,496,496
BEGIN DESCRIPTION:
Long Branch 22.0
END DESCRIPTION:
XS GIS Cut Line= 3
        1366855.      6841487.98      1366841.96      6841252.04
      1366254.97      6840637.97
#Sta/Elev= 30
  4763.7 2214.22  4841.1 2211.32  4873.9 2210.33  4883.9 2210.94  4939.4 2208.66
    4954 2206.99    4964 2203.61    4974  2195.3    4984 2188.51  4985.5  2186.1
    4986  2185.6  5002.5  2186.1  5007.7 2191.72  5014.9 2193.73  5029.1 2194.26
  5079.9 2192.83  5128.1 2193.67  5148.2 2194.83  5177.5 2196.36  5198.9 2198.81
  5276.6 2204.09    5319  2205.8  5389.8 2205.78  5432.3 2204.89  5509.9 2205.14
  5651.5 2208.12  5708.1 2210.68    5715 2211.58  5736.4 2211.93  5849.5 2220.25
#Mann= 7 ,-1 , 0
  4763.7     .07       0  4841.1    .035       0  4939.4     .07       0
  4985.5     .07       0  5002.5     .07       0  5079.9     .16       0
  5148.2     .07       0
Bank Sta=4985.5,5002.5
XS Rating Curve= 0 ,0
Exp/Cntr=0.3,0.1

Type RM Length L Ch R = 1 ,11587   ,992,992,992
BEGIN DESCRIPTION:
Long Branch 21.0
END DESCRIPTION:
XS GIS Cut Line= 3
        1367255.      6841388.02      1367184.94      6840988.01
      1366204.99      6840287.99
#Sta/Elev= 30
  4593.9  2209.8  4715.7 2207.84  4847.7 2203.74  4878.2 2201.09  4898.5 2194.08
  4918.8 2190.64  5007.3 2191.32  5013.5  2190.4  5019.7 2184.82  5020.2 2184.32
  5036.7 2184.82  5036.8 2185.52    5129 2196.35  5221.2 2200.84  5330.5 2202.48
  5416.6 2201.27  5559.1 2202.04  5594.8 2201.28    5666 2202.04    5725 2204.16
  5737.3 2205.66  5752.1 2205.26  5909.4 2217.43  5946.2  2220.8  5953.6 2222.68
  5983.1 2224.66  5989.2 2226.02  6024.9 2228.78  6104.7 2237.55  6204.3 2245.53
#Mann= 3 ,-1 , 0
  4593.9     .07       0  5019.7     .07       0  5036.7     .07       0
Bank Sta=5019.7,5036.7
XS Rating Curve= 0 ,0
Exp/Cntr=0.3,0.1

Type RM Length L Ch R = 1 ,10595   ,498,498,498
BEGIN DESCRIPTION:
Long Branch 20.0
END DESCRIPTION:
XS GIS Cut Line= 3
      1367604.99      6841187.96      1367401.48        6840487.
      1366805.03      6839888.03
#Sta/Elev= 30
  4270.1 2204.44  4537.3 2198.85  4734.5  2197.7  4832.4 2195.29  4884.4 2197.09
  4932.4 2195.22  4957.3 2192.54  4977.6 2187.48  4988.5 2185.17    5000 2184.39
  5002.4 2179.75  5002.9 2179.25  5019.5 2179.75  5032.2 2184.86  5039.2 2186.28
  5088.7 2185.83  5102.9 2186.78  5138.2 2185.56    5206 2187.33  5230.1 2188.73
  5258.4 2193.01  5265.5 2192.39  5272.6 2193.83  5279.7 2192.89  5286.7 2194.11
  5293.8 2193.11  5307.9 2193.59  5654.4 2209.68  5795.8 2222.31  5845.3 2225.41
#Mann= 6 ,-1 , 0
  4270.1     .07       0  4734.5     .16       0  4977.6     .12       0
  5002.4     .07       0  5019.5     .12       0    5206     .07       0
Bank Sta=5002.4,5019.5
XS Rating Curve= 0 ,0
Exp/Cntr=0.3,0.1

Type RM Length L Ch R = 1 ,10097   ,497,497,497
BEGIN DESCRIPTION:
Long Branch 19.0
END DESCRIPTION:
XS GIS Cut Line= 3
      1367854.99      6841237.97      1367357.25      6840131.58
      1367455.02      6839937.96
#Sta/Elev= 30
  3786.8 2206.74    3876 2205.61  3907.4 2203.52  3916.9 2204.21  3968.6 2202.11
  3984.1 2203.08  4234.3 2197.66  4460.9 2196.08  4557.2 2194.96  4603.5 2192.87
    4637 2189.69    4673 2186.57  4807.3 2185.41    4834 2185.34  5007.8 2183.23
  5024.5  2180.7  5030.1  2181.5  5037.6 2180.08  5038.2 2177.92  5038.7 2177.42
  5055.4 2177.92    5060 2178.17  5069.1 2181.24  5074.7 2180.46  5091.4 2186.49
  5119.3 2193.56  5141.6 2195.76  5175.6 2201.24  5194.4 2203.05  5216.9 2203.06
#Mann= 8 ,-1 , 0
  3786.8     .07       0  4460.9     .16       0    4637     .12       0
  4807.3     .16       0    4834     .12       0  5038.2     .07       0
  5055.4     .12       0  5175.6     .07       0
Bank Sta=5038.2,5055.4
XS Rating Curve= 0 ,0
Exp/Cntr=0.3,0.1

Type RM Length L Ch R = 1 ,9600    ,496,496,496
BEGIN DESCRIPTION:
Long Branch 18.0
END DESCRIPTION:
XS GIS Cut Line= 3
        1367855.      6840987.98      1367774.98      6840288.04
        1367705.      6839737.97
#Sta/Elev= 30
  4295.5 2201.39    4376  2199.6  4406.2 2197.94  4436.4 2197.87  4466.6 2195.19
  4513.7 2193.85    4527 2194.43  4587.4 2193.24  4748.4 2194.09  4775.4  2192.9
  4781.7 2193.82  4808.8 2192.91  4848.1 2189.42  4889.3 2184.38  4939.6 2182.97
  4949.7 2181.98  4960.3 2180.24  4961.2 2176.15  4961.7 2175.65  4978.4 2176.15
  4997.5 2181.59  5030.3 2183.09  5050.4 2188.34  5060.5 2189.96  5181.7 2194.48
  5357.2 2200.55  5362.9 2201.79  5413.3 2205.17  5504.1 2214.91  5554.5 2222.49
#Mann= 6 ,-1 , 0
  4295.5     .07       0  4775.4     .16       0  4848.1     .12       0
  4961.2     .07       0  4978.4     .12       0  5181.7     .07       0
Bank Sta=4961.2,4978.4
XS Rating Curve= 0 ,0
Exp/Cntr=0.3,0.1

Type RM Length L Ch R = 1 ,9104    ,497,497,497
BEGIN DESCRIPTION:
Long Branch 17.0
END DESCRIPTION:
XS GIS Cut Line= 3
       1367945.6      6841004.55      1368239.28      6840288.97
      1368104.99      6839787.96
#Sta/Elev= 30
  4226.5  2202.1  4393.2 2192.55  4601.1 2190.93    4684 2189.17  4744.9 2186.28
  4761.3 2184.08  4790.7 2182.61  4806.5 2179.61  4814.7  2181.4  4873.5 2177.82
  4921.1  2179.4  4957.8 2181.11  4968.6 2179.49  4971.6 2172.75  4972.1 2172.25
  4988.8 2172.75  4997.8 2176.03  5003.1 2176.03  5011.4 2179.07  5021.7 2180.75
  5036.5 2180.32  5071.4 2184.64  5076.6 2183.62  5125.2 2188.05  5306.3 2191.28
  5394.4 2196.45  5404.8 2195.96  5426.4 2199.31  5461.2 2207.32  5518.7  2211.5
#Mann= 5 ,-1 , 0
  4226.5     .07       0  4744.9     .16       0  4921.1     .07       0
  4971.6     .07       0  4988.8     .07       0
Bank Sta=4971.6,4988.8
XS Rating Curve= 0 ,0
Exp/Cntr=0.3,0.1

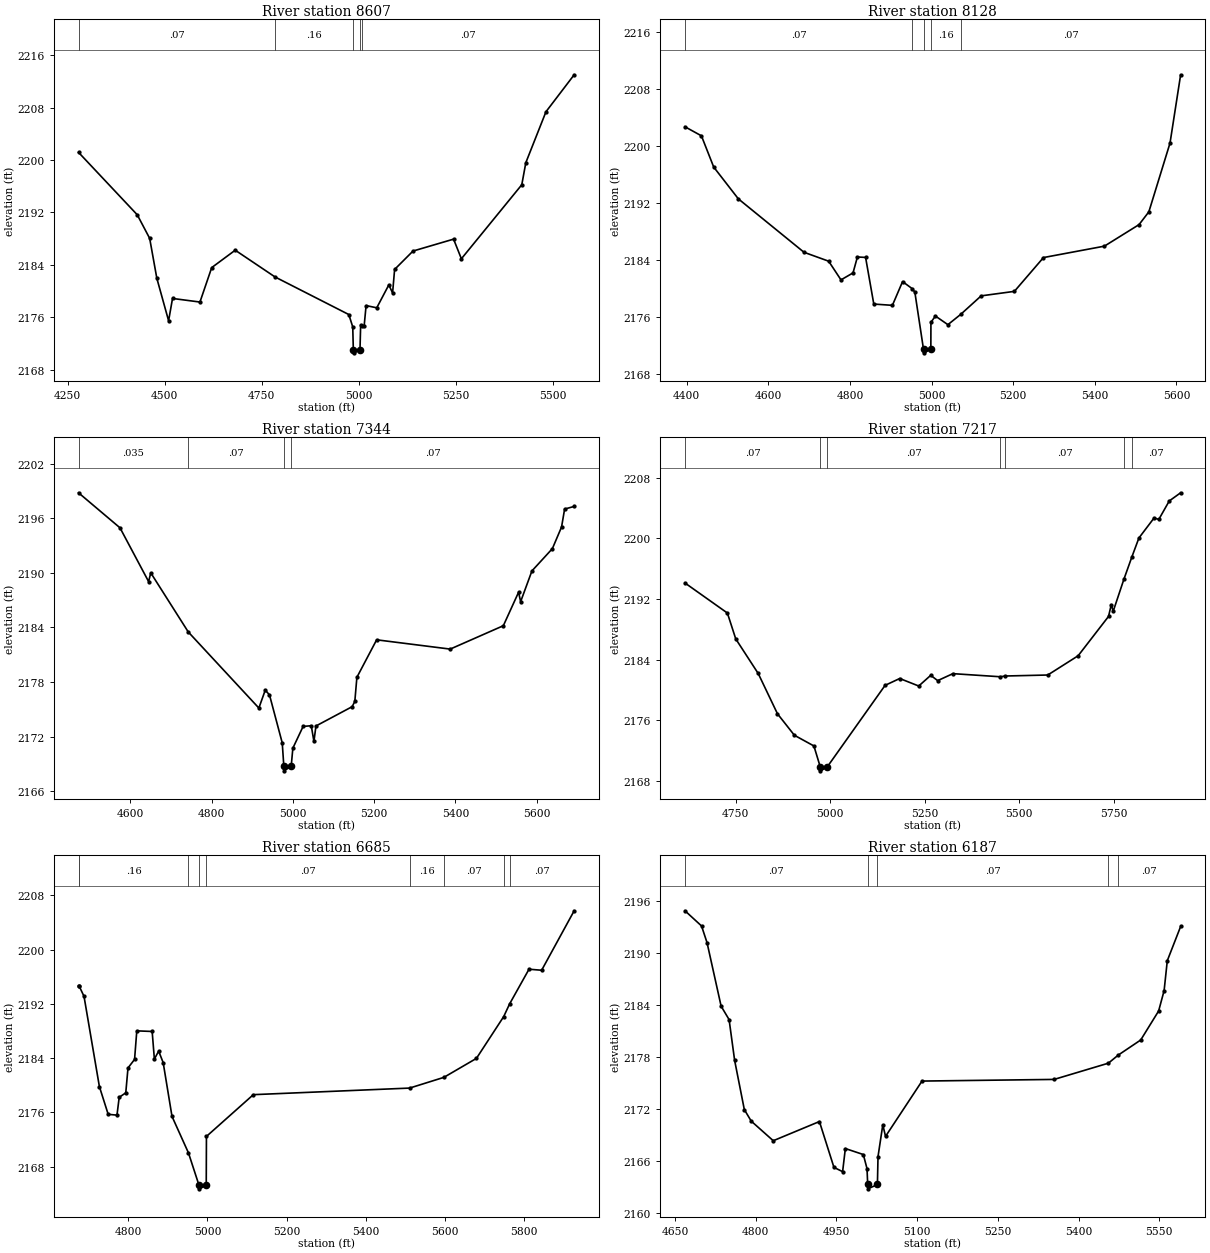
Type RM Length L Ch R = 1 ,8607    ,479,479,479
BEGIN DESCRIPTION:
Long Branch 16.0
END DESCRIPTION:
XS GIS Cut Line= 3
      1368554.99      6840937.96      1368454.77      6840222.85
      1368305.01      6839688.02
#Sta/Elev= 30
  4277.9 2201.18  4429.3 2191.64  4461.3 2188.04  4479.8 2181.93  4510.1 2175.45
  4520.2 2178.86  4590.9 2178.31  4621.2 2183.57  4681.8 2186.23  4784.5 2182.14
  4974.6  2176.4  4984.7 2174.51  4986.2 2171.05  4986.7 2170.55  5003.4 2171.05
  5005.1 2174.81  5009.2 2174.71    5014 2174.59  5019.1 2177.77  5046.6 2177.43
  5077.7 2180.93  5087.4  2179.7  5092.6 2183.29    5140  2186.1  5244.6 2187.92
  5264.7 2184.92  5420.4 2196.23  5430.8  2199.6  5482.7 2207.38  5555.4 2213.03
#Mann= 5 ,-1 , 0
  4277.9     .07       0  4784.5     .16       0  4986.2     .07       0
  5003.4     .16       0  5009.2     .07       0
Bank Sta=4986.2,5003.4
XS Rating Curve= 0 ,0
Exp/Cntr=0.3,0.1

Type RM Length L Ch R = 1 ,8128    ,784,784,784
BEGIN DESCRIPTION:
Long Branch 15.0
END DESCRIPTION:
XS GIS Cut Line= 3
        1368655.      6840938.03      1368720.33      6840337.38
      1368604.99      6839737.97
#Sta/Elev= 30
  4395.8 2202.67  4436.1  2201.4  4466.2 2197.02  4526.6 2192.56  4687.5 2185.07
  4747.9 2183.82  4778.1  2181.2  4807.6 2182.18  4818.3 2184.41  4838.4 2184.35
  4858.5 2177.81  4904.1 2177.63    4929 2180.96  4952.6 2179.97  4959.1 2179.48
  4980.3 2171.47  4980.8 2170.97  4998.3 2171.47  4998.5 2175.25  5009.5 2176.13
  5040.1 2174.92  5071.4 2176.36  5121.6 2178.96    5203 2179.59  5274.3 2184.33
  5423.6 2185.93  5508.5 2188.95  5532.5 2190.74  5584.4 2200.39  5610.4 2209.96
#Mann= 5 ,-1 , 0
  4395.8     .07       0  4952.6     .16       0  4980.3     .07       0
  4998.3     .16       0  5071.4     .07       0
Bank Sta=4980.3,4998.3
XS Rating Curve= 0 ,0
Exp/Cntr=0.3,0.1

Type RM Length L Ch R = 1 ,7344    ,127,127,127
BEGIN DESCRIPTION:
Long Branch 14.0
END DESCRIPTION:
XS GIS Cut Line= 3
      1368948.62      6840916.67      1369104.73      6840413.11
      1369173.33      6839724.62
#Sta/Elev= 30
  4472.8 2198.79  4574.8 2194.94  4645.2 2189.03  4650.5 2189.99  4742.8 2183.49
  4916.4 2175.13  4932.1  2177.1  4942.5 2176.58  4973.9  2171.3  4977.8 2168.73
  4978.3 2168.23  4995.9 2168.73    5000 2170.72  5025.2 2173.11  5045.3 2173.19
  5051.8 2171.46  5056.8 2173.16  5145.8 2175.28  5152.4 2175.86  5157.5 2178.51
  5206.1 2182.63    5387 2181.61  5517.7 2184.18  5555.2 2187.86  5560.2 2186.82
    5588  2190.2  5638.3 2192.65  5660.9 2195.03  5668.4    2197  5691.9 2197.29
#Mann= 4 ,-1 , 0
  4472.8    .035       0  4742.8     .07       0  4977.8     .07       0
  4995.9     .07       0
Bank Sta=4977.8,4995.9
XS Rating Curve= 0 ,0
Exp/Cntr=0.3,0.1

Type RM Length L Ch R = 1 ,7217    ,532,532,532
BEGIN DESCRIPTION:
Long Branch 13.0
END DESCRIPTION:
XS GIS Cut Line= 3
        1369105.        6840888.      1369178.27      6840511.36
        1369255.      6839588.04
#Sta/Elev= 30
  4616.3  2194.1  4728.4 2190.14  4750.5 2186.73  4809.9 2182.17  4860.8 2176.86
  4905.5 2174.03  4957.1 2172.62    4974 2169.84  4974.5 2169.34  4992.1 2169.84
  5145.3 2180.61    5184 2181.51  5234.2 2180.52  5265.9 2181.93  5284.3 2181.23
  5324.5 2182.15    5450 2181.74  5463.3 2181.84  5575.3 2181.97  5655.6 2184.51
  5735.9 2189.69  5743.2 2191.25  5748.2 2190.36  5776.3 2194.56  5797.5 2197.52
  5816.2 2200.03  5856.3 2202.67  5868.8 2202.48  5896.4 2204.91  5926.5 2205.99
#Mann= 7 ,-1 , 0
  4616.3     .07       0    4974     .07       0  4992.1     .07       0
    5450     .16       0  5463.3     .07       0  5776.3    .035       0
  5797.5     .07       0
Bank Sta=4974,4992.1
XS Rating Curve= 0 ,0
Exp/Cntr=0.3,0.1

Type RM Length L Ch R = 1 ,6685    ,498,498,498
BEGIN DESCRIPTION:
Long Branch 12.0
END DESCRIPTION:
XS GIS Cut Line= 3
      1369805.02      6840638.01      1369515.49      6840489.49
      1369305.01      6839588.03
#Sta/Elev= 30
  4674.6 2194.68  4675.7 2194.68  4688.5  2193.1  4727.3 2179.79  4749.5  2175.7
  4771.7 2175.58  4777.3 2178.21  4793.9 2178.87  4799.5 2182.54  4816.1  2183.8
  4821.7 2188.01  4860.5 2187.92  4866.1 2183.85  4876.9 2185.02  4888.3 2183.33
  4910.6 2175.39  4952.2    2170  4978.9 2165.21  4979.4 2164.71    4997 2165.21
  4997.5 2172.44  5115.9  2178.6  5510.3 2179.57  5596.8 2181.15    5679 2183.95
  5747.9 2190.12  5762.7 2191.98  5811.7  2197.1  5843.6 2196.95  5925.7 2205.72
#Mann= 9 ,-1 , 0
  4674.6     .07       0  4675.7     .16       0  4952.2     .07       0
  4978.9     .07       0    4997     .07       0  5510.3     .16       0
  5596.8     .07       0  5747.9    .035       0  5762.7     .07       0
Bank Sta=4978.9,4997
XS Rating Curve= 0 ,0
Exp/Cntr=0.3,0.1

Type RM Length L Ch R = 1 ,6187    ,320,320,320
BEGIN DESCRIPTION:
Long Branch 11.0
END DESCRIPTION:
XS GIS Cut Line= 3
        1369855.      6840588.01      1369928.36      6840264.73
        1369805.      6839687.98
#Sta/Elev= 30
  4668.5 2194.82  4699.3 2193.07  4709.5 2191.15  4735.7 2183.83  4750.5 2182.29
  4760.8 2177.59  4778.8 2171.93  4791.6  2170.6  4832.6 2168.34  4918.4 2170.55
  4945.4 2165.27  4961.5 2164.78  4966.6 2167.44    5000 2166.75  5006.9 2165.12
  5008.1  2163.3  5008.6  2162.8  5026.2  2163.3  5027.3 2166.51  5036.2 2170.17
  5041.3 2168.84  5109.1 2175.21  5354.6  2175.4  5455.5 2177.27  5473.8  2178.2
  5515.6 2179.94  5548.9 2183.28  5559.1 2185.63    5565 2189.07  5589.8 2193.01
#Mann= 5 ,-1 , 0
  4668.5     .07       0  5008.1     .07       0  5026.2     .07       0
  5455.5     .16       0  5473.8     .07       0
Bank Sta=5008.1,5026.2
XS Rating Curve= 0 ,0
Exp/Cntr=0.3,0.1

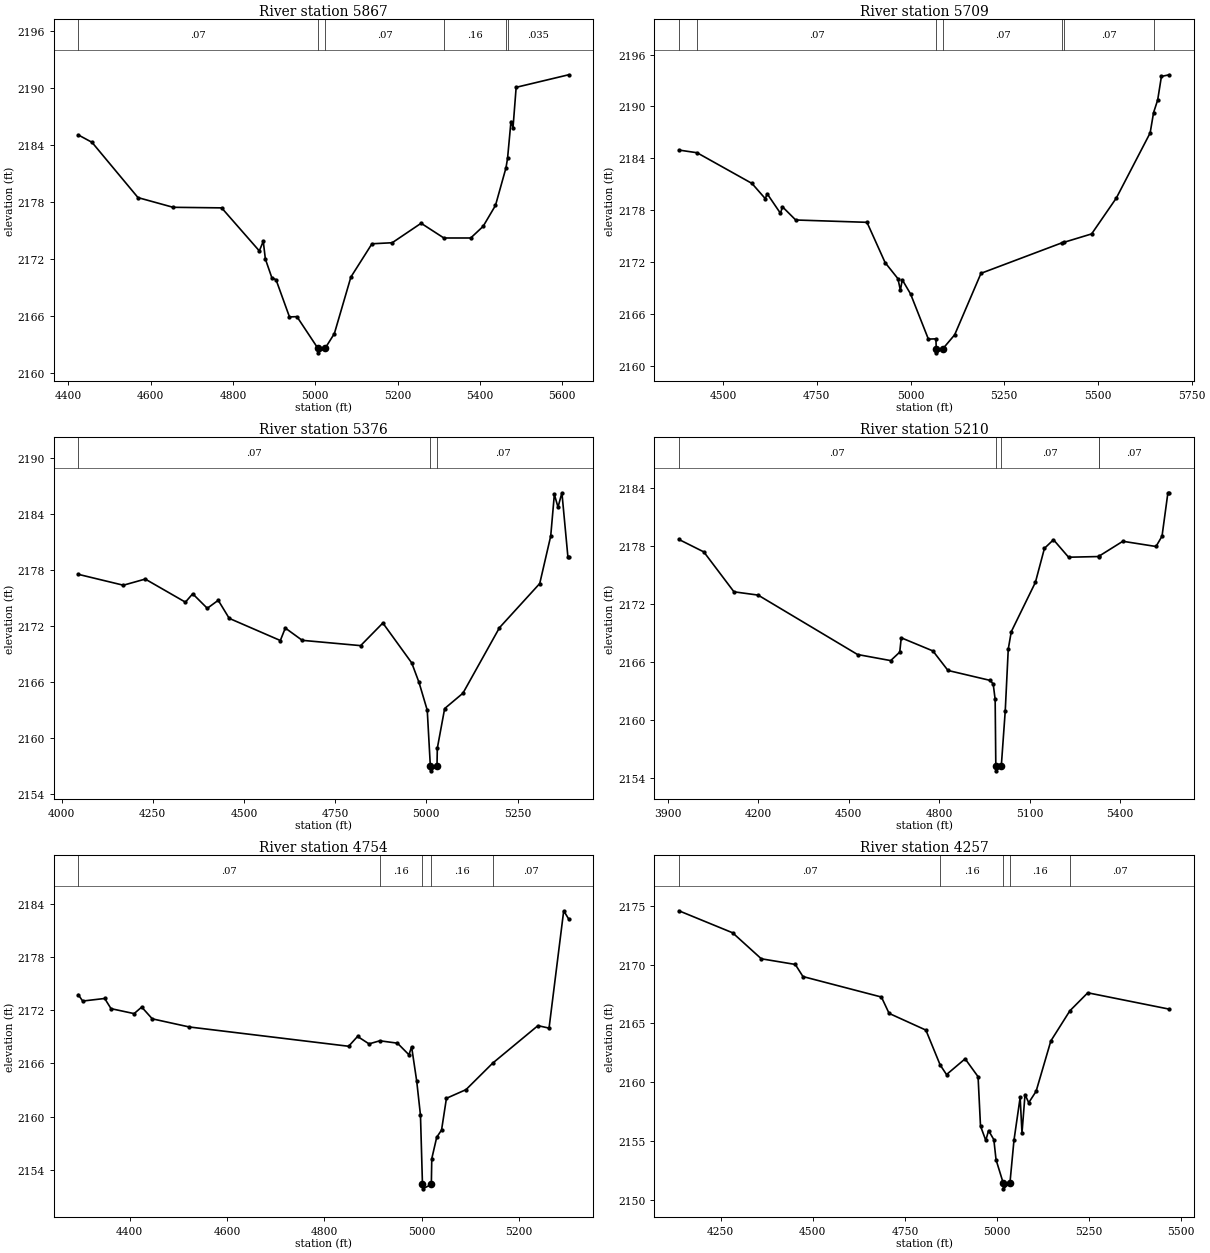
Type RM Length L Ch R = 1 ,5867    ,158,158,158
BEGIN DESCRIPTION:
Long Branch 10.1
END DESCRIPTION:
XS GIS Cut Line= 3
      1370069.14      6840670.85      1370171.66      6840104.25
      1370117.99      6839490.99
#Sta/Elev= 30
  4424.2 2185.08  4457.6  2184.3  4569.4 2178.48  4654.7 2177.46  4772.6  2177.4
  4864.1 2172.87  4873.7 2173.88  4878.8 2172.02  4894.6 2170.04  4904.7 2169.84
  4937.4 2165.92  4955.5 2165.95  5006.1 2162.64  5006.6 2162.14  5024.3 2162.64
  5046.4 2164.16  5086.6 2170.12  5137.8 2173.62    5187 2173.73  5257.2 2175.78
  5312.5 2174.23  5377.7 2174.23  5407.8 2175.45  5437.9 2177.66  5463.3  2181.6
  5467.2  2182.6  5475.5 2186.49  5480.5 2185.84  5488.1 2190.09  5615.6 2191.41
#Mann= 6 ,-1 , 0
  4424.2     .07       0  5006.1     .07       0  5024.3     .07       0
  5312.5     .16       0  5463.3     .07       0  5467.2    .035       0
Bank Sta=5006.1,5024.3
XS Rating Curve= 0 ,0
Exp/Cntr=0.3,0.1

Type RM Length L Ch R = 1 ,5709    ,333,333,333
BEGIN DESCRIPTION:
Long Branch 10.0
END DESCRIPTION:
XS GIS Cut Line= 3
      1370141.73      6840783.79      1370296.49      6840185.38
      1370244.29      6839497.06
#Sta/Elev= 30
  4381.9 2184.95  4430.3 2184.64  4576.8 2181.09  4612.3 2179.33  4617.5 2179.89
  4652.9 2177.63  4658.1 2178.39  4693.5 2176.86  4883.7 2176.59  4932.1 2171.93
  4966.3 2170.07  4972.8 2168.73  4977.9 2169.94    5000  2168.3  5047.5 2163.08
  5067.6 2163.11  5068.5 2161.99    5069 2161.49  5086.7 2161.99  5117.7 2163.58
  5187.9 2170.69  5403.9 2174.22  5408.7 2174.27  5483.1 2175.25    5549  2179.4
  5639.2 2186.93  5648.4 2189.29  5659.3 2190.74  5669.3 2193.47  5690.3 2193.66
#Mann= 7 ,-1 , 0
  4381.9    .035       0  4430.3     .07       0  5068.5     .07       0
  5086.7     .07       0  5403.9     .16       0  5408.7     .07       0
  5648.4    .035       0
Bank Sta=5068.5,5086.7
XS Rating Curve= 0 ,0
Exp/Cntr=0.3,0.1

Type RM Length L Ch R = 1 ,5376    ,166,166,166
BEGIN DESCRIPTION:
Long Branch 9.1
END DESCRIPTION:
XS GIS Cut Line= 3
      1370561.39      6840921.47      1370525.34      6839968.06
      1370498.43      6839578.98
#Sta/Elev= 30
  4045.9 2177.55  4169.5 2176.38  4229.5 2177.04  4339.6 2174.56  4359.6 2175.46
  4399.6  2173.9  4429.6 2174.76  4459.7 2172.82  4599.8 2170.44  4613.4 2171.78
  4659.8 2170.46  4819.9 2169.89  4880.8 2172.32    4960 2168.03    4980 2165.93
  5002.5 2162.95    5011 2156.94  5011.5 2156.44  5029.2 2156.94  5030.1 2158.87
  5050.2 2163.13  5100.3 2164.78  5200.5 2171.82  5310.8 2176.56  5340.9 2181.66
  5350.9 2186.14  5360.9 2184.76  5371.6 2186.31    5388 2179.43    5390 2179.43
#Mann= 3 ,-1 , 0
  4045.9     .07       0    5011     .07       0  5029.2     .07       0
Bank Sta=5011,5029.2
XS Rating Curve= 0 ,0
Exp/Cntr=0.3,0.1

Type RM Length L Ch R = 1 ,5210    ,456,456,456
BEGIN DESCRIPTION:
Long Branch 9.0
END DESCRIPTION:
XS GIS Cut Line= 3
      1370673.55      6840950.64       1370639.6      6839887.28
      1370617.11      6839323.93
#Sta/Elev= 30
  3936.1  2178.7  4018.8 2177.41  4118.8 2173.28  4198.9 2172.94    4529 2166.79
  4639.1 2166.16  4669.1 2167.04  4674.1 2168.52  4779.2 2167.16  4829.2 2165.14
  4969.3 2164.11  4979.3 2163.74  4985.8 2162.14    4988 2155.25  4988.5 2154.75
  5006.2 2155.25  5019.3 2160.96  5029.3 2167.35  5039.3 2169.15  5119.4 2174.26
  5149.4 2177.78  5179.4 2178.67  5229.5 2176.86  5329.2 2176.93  5330.6 2176.97
  5409.6 2178.51  5519.7 2177.97  5539.7 2179.04  5559.2 2183.53  5563.8 2183.53
#Mann= 5 ,-1 , 0
  3936.1     .07       0    4988     .07       0  5006.2     .07       0
  5329.2    .035       0  5330.6     .07       0
Bank Sta=4988,5006.2
XS Rating Curve= 0 ,0
Exp/Cntr=0.3,0.1

Type RM Length L Ch R = 1 ,4754    ,497,497,497
BEGIN DESCRIPTION:
Long Branch 8.0
END DESCRIPTION:
XS GIS Cut Line= 3
      1370705.01      6840687.98      1370980.14      6840038.56
        1371005.      6839737.98
#Sta/Elev= 30
  4294.7 2173.77  4303.8 2173.05    4349 2173.34    4362 2172.19  4409.4 2171.63
    4425 2172.37  4446.7 2171.04  4522.7 2170.12  4849.9 2167.94  4868.2 2169.05
  4891.8 2168.21  4913.9 2168.56  4950.1 2168.29  4973.7 2166.98  4979.2 2167.88
  4989.7 2163.99  4997.4 2160.14  5001.5 2152.33    5002 2151.83  5019.7 2152.33
  5020.6 2155.24  5030.7 2157.65  5040.7 2158.48  5050.7 2162.06  5090.9 2163.04
  5145.8 2166.04  5238.6 2170.27  5261.4 2169.99  5291.5 2183.25  5301.6 2182.33
#Mann= 5 ,-1 , 0
  4294.7     .07       0  4913.9     .16       0  5001.5     .07       0
  5019.7     .16       0  5145.8     .07       0
Bank Sta=5001.5,5019.7
XS Rating Curve= 0 ,0
Exp/Cntr=0.3,0.1

Type RM Length L Ch R = 1 ,4257    ,497,497,497
BEGIN DESCRIPTION:
Long Branch 7.0
END DESCRIPTION:
XS GIS Cut Line= 3
      1370750.99      6840848.75      1371313.42      6840193.94
      1371288.65       6839727.1
#Sta/Elev= 30
  4136.8 2174.57  4282.5  2172.7  4360.4 2170.49  4452.6 2170.01  4473.4 2168.98
  4686.3 2167.24  4707.2 2165.85    4807 2164.43  4845.7 2161.47    4863 2160.65
  4913.5 2161.99  4948.6 2160.47  4955.2 2156.28  4969.5 2155.06  4977.1 2155.89
  4991.4 2155.12  4997.4 2153.41  5016.8 2151.44  5017.3 2150.94  5035.1 2151.44
    5046 2155.06  5062.8 2158.71  5067.8 2155.68    5076 2158.95  5086.1 2158.26
  5106.1 2159.23  5146.1 2163.51  5197.7 2166.07  5246.3  2167.6  5467.5 2166.21
#Mann= 5 ,-1 , 0
  4136.8     .07       0  4845.7     .16       0  5016.8     .07       0
  5035.1     .16       0  5197.7     .07       0
Bank Sta=5016.8,5035.1
XS Rating Curve= 0 ,0
Exp/Cntr=0.3,0.1

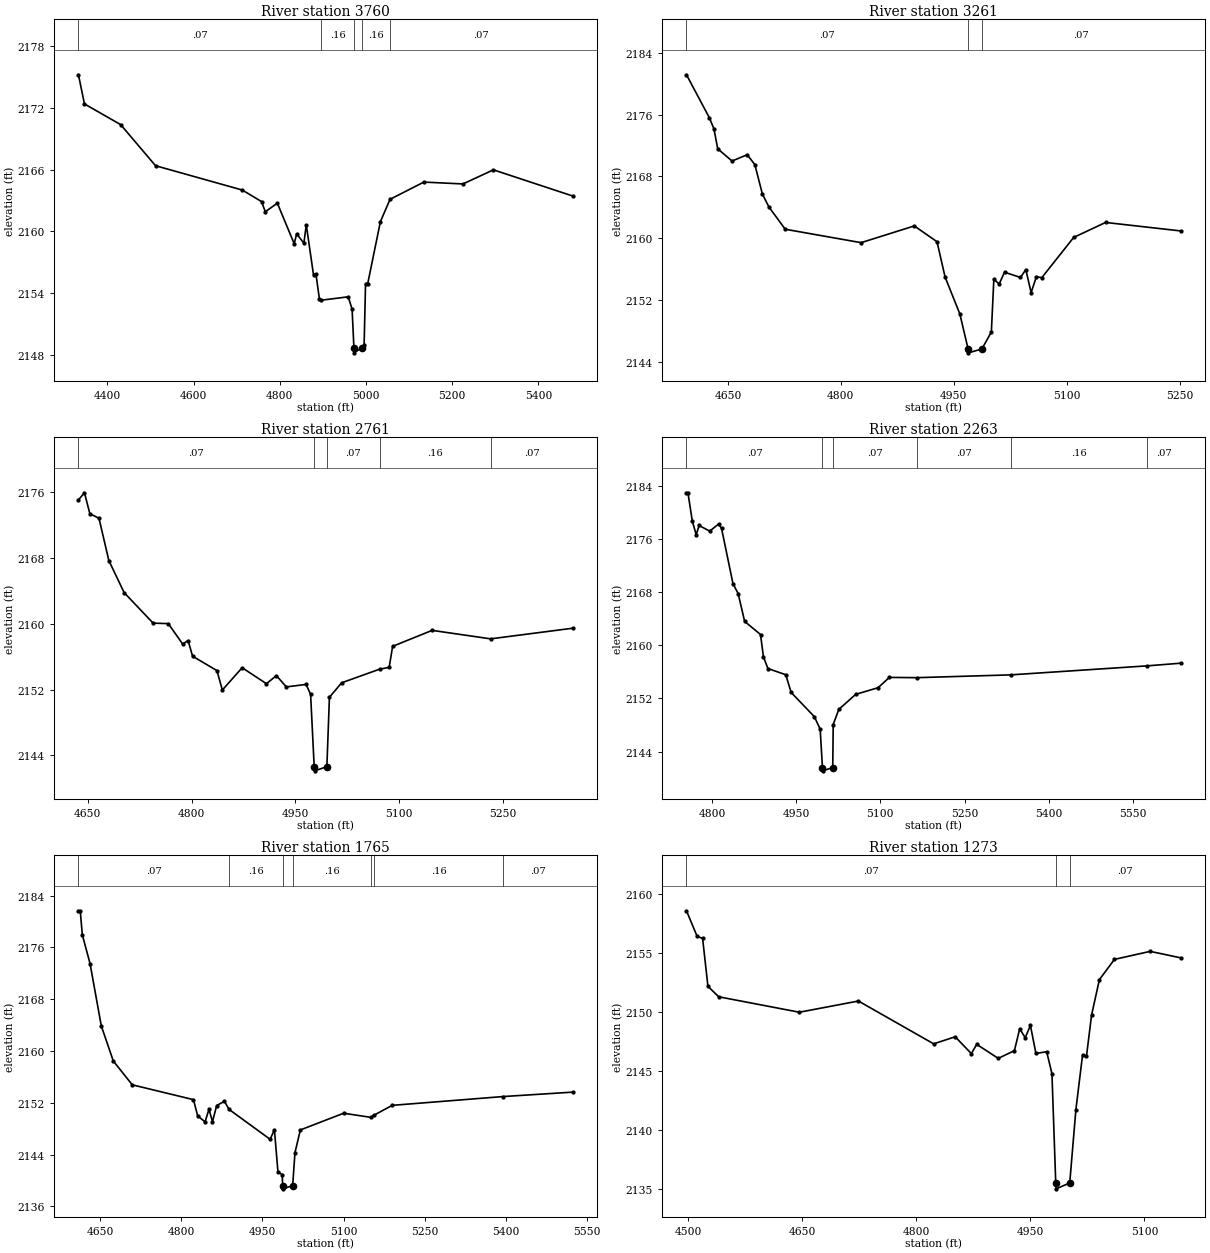
Type RM Length L Ch R = 1 ,3760    ,499,499,499
BEGIN DESCRIPTION:
Long Branch 6.0
END DESCRIPTION:
XS GIS Cut Line= 3
      1371354.98      6840788.04      1371652.91      6840191.16
       1371591.9      6839715.56
#Sta/Elev= 30
  4332.9  2175.2  4346.9 2172.37  4430.8 2170.36  4511.8 2166.37  4712.9 2164.01
  4757.7 2162.89  4766.4  2161.9  4794.4 2162.73  4833.5 2158.79  4839.1 2159.75
  4855.9 2158.85  4861.5 2160.63  4878.3 2155.76  4883.9 2155.87  4891.8 2153.47
  4896.1 2153.31  4958.8 2153.64  4967.8 2152.44    4972  2148.7  4972.5  2148.2
  4990.3  2148.7  4995.7 2148.98    4999 2154.93  5004.1 2154.93  5033.4 2160.93
  5055.9 2163.11  5134.3 2164.78    5225  2164.6  5295.6 2165.97  5479.5 2163.43
#Mann= 5 ,-1 , 0
  4332.9     .07       0  4896.1     .16       0    4972     .07       0
  4990.3     .16       0  5055.9     .07       0
Bank Sta=4972,4990.3
XS Rating Curve= 0 ,0
Exp/Cntr=0.3,0.1

Type RM Length L Ch R = 1 ,3261    ,500,500,500
BEGIN DESCRIPTION:
Long Branch 5.0
END DESCRIPTION:
XS GIS Cut Line= 3
        1371805.      6840987.99      1371858.74      6840586.48
      1372036.54      6840408.45
#Sta/Elev= 30
  4594.9 2181.17  4625.2 2175.62  4631.4 2174.15  4636.4 2171.58  4655.4 2169.99
  4675.6 2170.81  4685.7 2169.53  4695.8  2165.7  4704.4 2164.04  4726.1 2161.15
  4826.9 2159.41  4897.6 2161.58  4927.8 2159.53  4938.5 2154.96  4958.1 2150.18
  4969.1 2145.63  4969.6 2145.13  4987.4 2145.63    5000 2147.83  5003.3 2154.66
  5010.4 2154.06  5017.5 2155.58  5038.7  2154.9  5045.8 2155.92  5052.8 2152.94
  5059.9    2155    5067 2154.87  5109.4 2160.09  5151.8 2162.03  5251.6 2160.93
#Mann= 3 ,-1 , 0
  4594.9     .07       0  4969.1     .07       0  4987.4     .07       0
Bank Sta=4969.1,4987.4
XS Rating Curve= 0 ,0
Exp/Cntr=0.3,0.1

Type RM Length L Ch R = 1 ,2761    ,498,498,498
BEGIN DESCRIPTION:
Long Branch 4.0
END DESCRIPTION:
XS GIS Cut Line= 3
      1371912.18      6841057.65      1372191.22      6840824.85
      1372225.92      6840475.97
#Sta/Elev= 30
  4636.6 2175.05  4645.3 2175.91  4653.1 2173.37  4666.3 2172.81  4680.5 2167.68
  4702.6 2163.78  4744.5 2160.07  4766.4 2160.01  4787.2 2157.53    4795 2157.95
  4801.5 2156.05  4836.7  2154.3  4844.5 2151.94  4873.1 2154.65  4908.2 2152.71
  4922.6 2153.69  4936.9 2152.32  4965.5 2152.62    4972 2151.42  4977.2 2142.62
  4977.7 2142.12  4995.5 2142.62  4999.2 2151.06  5016.9 2152.82  5071.9 2154.48
  5085.5 2154.69  5090.5 2157.25  5147.6 2159.19  5232.1 2158.16  5350.6 2159.45
#Mann= 5 ,-1 , 0
  4636.6     .07       0  4977.2     .07       0  4995.5     .07       0
  5071.9     .16       0  5232.1     .07       0
Bank Sta=4977.2,4995.5
XS Rating Curve= 0 ,0
Exp/Cntr=0.3,0.1

Type RM Length L Ch R = 1 ,2263    ,498,498,498
BEGIN DESCRIPTION:
Long Branch 3.0
END DESCRIPTION:
XS GIS Cut Line= 3
      1372155.01        6841288.      1372391.93      6841224.03
      1372387.59      6840588.95
#Sta/Elev= 30
  4754.6 2182.99  4757.2 2182.99  4764.9 2178.75  4771.9 2176.67  4777.1 2178.06
    4796 2177.21  4811.8 2178.28    4817 2177.64  4837.5 2169.27  4846.6 2167.81
  4858.2 2163.61  4886.5 2161.63  4891.6 2158.31  4899.6 2156.51  4931.5 2155.57
    4941 2152.91  4982.5 2149.24  4992.8 2147.36  4996.8 2141.59  4997.3 2141.09
  5015.2 2141.59    5016 2148.07    5026 2150.35    5056 2152.61    5096 2153.62
    5116 2155.17  5164.9 2155.13    5332 2155.55  5575.4 2156.91  5635.1 2157.31
#Mann= 6 ,-1 , 0
  4754.6     .07       0  4996.8     .07       0  5015.2     .07       0
  5164.9     .07       0    5332     .16       0  5575.4     .07       0
Bank Sta=4996.8,5015.2
XS Rating Curve= 0 ,0
Exp/Cntr=0.3,0.1

Type RM Length L Ch R = 1 ,1765    ,492,492,492
BEGIN DESCRIPTION:
Long Branch 2.0
END DESCRIPTION:
XS GIS Cut Line= 3
      1372554.99      6841588.01      1372855.03      6841338.08
      1372869.58      6840814.38
#Sta/Elev= 30
  4609.5 2181.66  4612.8 2181.66  4616.7 2177.95    4631 2173.49  4651.8 2163.87
    4674 2158.45  4709.1 2154.77  4822.3 2152.48  4830.2 2149.95  4843.8 2149.05
    4851 2150.99  4857.5 2149.09  4865.3 2151.57  4879.6 2152.23  4888.2 2150.97
  4964.2 2146.35  4972.1 2147.84  4978.6 2141.36  4986.4  2140.9  4987.5  2139.2
    4988  2138.7  5005.9  2139.2  5010.1 2144.29  5020.1  2147.8  5100.1 2150.38
    5151 2149.74  5156.8  2150.1  5190.1  2151.6  5395.5 2152.96  5523.9 2153.64
#Mann= 7 ,-1 , 0
  4609.5     .07       0  4888.2     .16       0  4987.5     .07       0
  5005.9     .16       0    5151     .07       0  5156.8     .16       0
  5395.5     .07       0
Bank Sta=4987.5,5005.9
XS Rating Curve= 0 ,0
Exp/Cntr=0.3,0.1

Type RM Length L Ch R = 1 ,1273    ,427,427,427
BEGIN DESCRIPTION:
Long Branch 1.0
END DESCRIPTION:
XS GIS Cut Line= 3
      1372955.03      6841687.97      1373315.19      6841337.55
      1373280.62      6841193.95
#Sta/Elev= 30
  4497.5 2158.61  4511.5 2156.44  4518.7 2156.27  4525.7 2152.21  4539.8 2151.32
    4646 2150.01  4723.7 2150.96  4822.7 2147.33    4851 2147.93  4872.3  2146.5
  4879.3 2147.29  4907.6  2146.1  4928.9 2146.75  4935.9 2148.61  4943.1 2147.85
    4950 2148.89  4957.2 2146.52  4971.4 2146.66  4978.3  2144.8  4983.3 2135.54
  4983.8 2135.04  5001.7 2135.54  5009.8 2141.75  5018.6  2146.4  5023.7 2146.26
  5030.4 2149.76  5040.7 2152.77  5060.5 2154.49  5107.6 2155.17  5147.7 2154.62
#Mann= 3 ,-1 , 0
  4497.5     .07       0  4983.3     .07       0  5001.7     .07       0
Bank Sta=4983.3,5001.7
XS Rating Curve= 0 ,0
Exp/Cntr=0.3,0.1