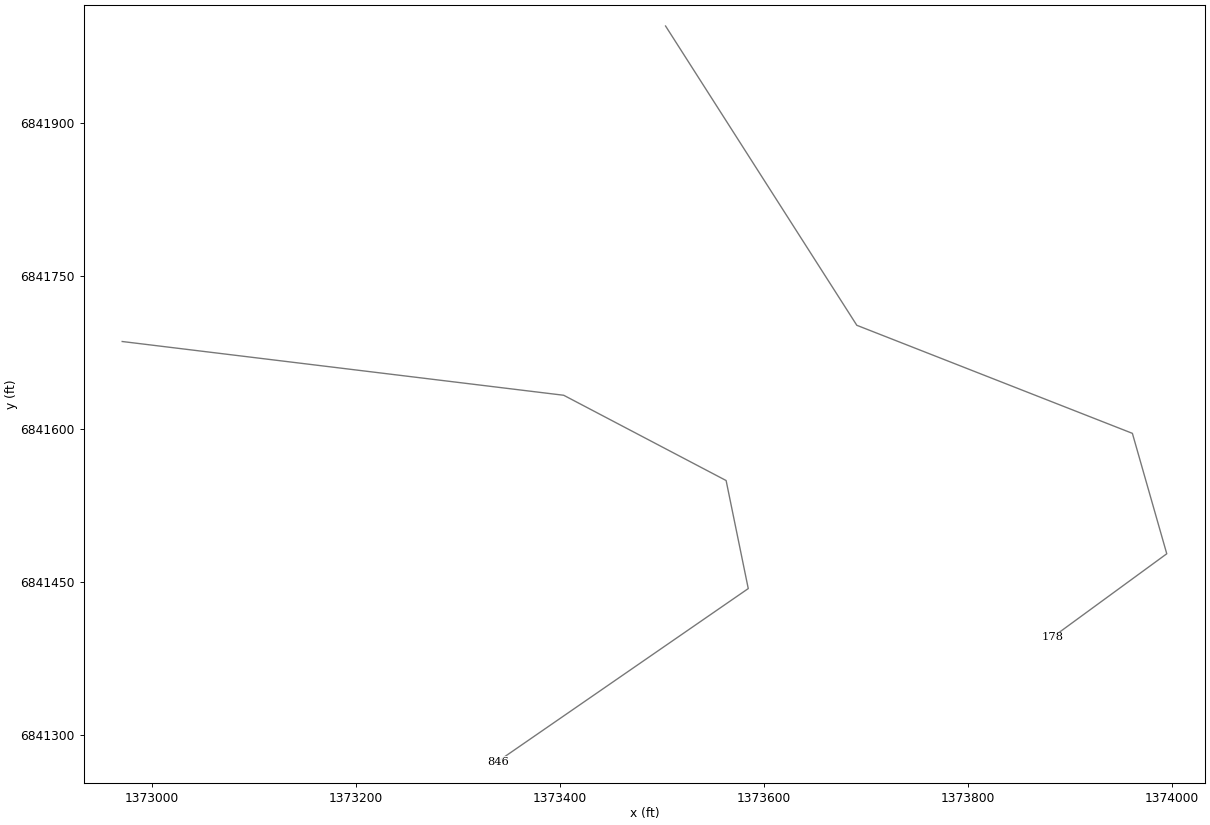
HEC-RAS study Long Branch.prj: Long Branch Base Level Engineering

--- Long Branch.g01 (geometry) --- (continued)

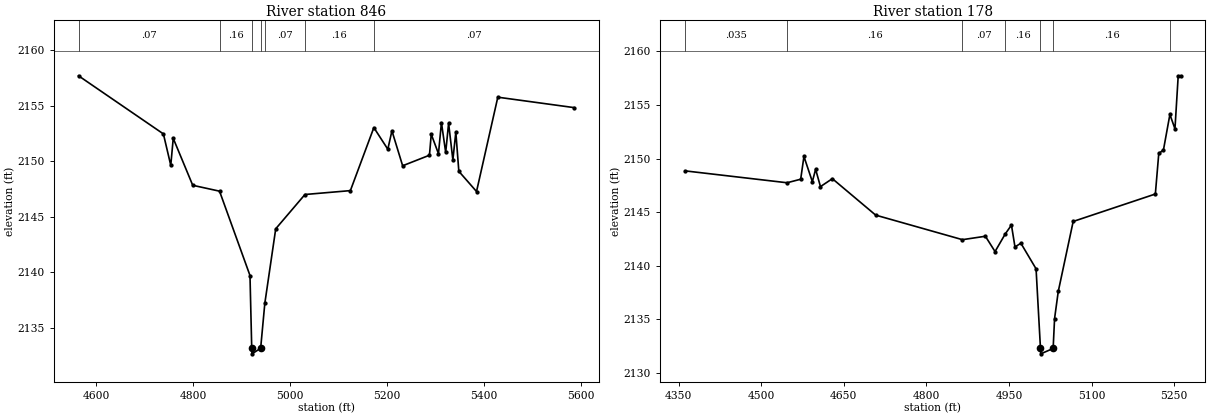
Type RM Length L Ch R = 1 ,846     ,668,668,668
BEGIN DESCRIPTION:
Long Branch 4467
END DESCRIPTION:
XS GIS Cut Line= 5
      1372971.18      6841686.02      1373403.98      6841633.32
      1373563.17      6841549.74      1373584.88      6841443.83
      1373339.21      6841274.29
#Sta/Elev= 30
    4564 2157.72  4739.1 2152.48  4754.3 2149.65  4759.4 2152.08  4799.6 2147.85
  4854.9 2147.32  4917.7 2139.72  4921.3 2133.16  4921.8 2132.66  4939.7 2133.16
  4948.3 2137.21  4970.8 2143.93  5031.1 2147.02  5124.8 2147.37  5173.2 2153.05
    5202  2151.1  5210.5 2152.76  5232.6 2149.61  5287.9 2150.56  5291.6 2152.45
  5306.5  2150.7  5312.6  2153.5  5321.4 2150.81  5327.4 2153.44  5336.2 2150.14
  5342.3 2152.64  5348.5 2149.11    5385 2147.29  5428.9 2155.79  5586.4 2154.85
#Mann= 7 ,-1 , 0
    4564     .07       0  4854.9     .16       0  4921.3     .07       0
  4939.7     .16       0  4948.3     .07       0  5031.1     .16       0
  5173.2     .07       0
Bank Sta=4921.3,4939.7
XS Rating Curve= 0 ,0
Exp/Cntr=0.3,0.1

Type RM Length L Ch R = 1 ,178     ,0,0,0
BEGIN DESCRIPTION:
Long Branch 4466
END DESCRIPTION:
XS GIS Cut Line= 5
      1373503.82      6841995.28       1373691.3      6841701.91
      1373961.42      6841595.99      1373995.12      6841477.95
      1373882.93      6841395.98
#Sta/Elev= 30
  4361.7 2148.86  4547.1 2147.75  4571.8 2148.08  4577.7  2150.2    4593 2147.85
  4598.9 2149.01  4607.7 2147.39  4629.3 2148.13    4708 2144.73  4865.5 2142.44
  4907.2 2142.76  4924.7 2141.33  4943.3 2142.98  4954.5  2143.8  4960.9 2141.76
  4971.6 2142.11  4999.2 2139.72  5007.2 2132.29  5007.7 2131.79  5030.2 2132.29
  5032.8 2135.08  5039.5 2137.61  5066.6 2144.14  5215.8  2146.7    5222 2150.48
  5230.5 2150.81  5242.2 2154.12  5251.4 2152.78  5257.3 2157.73  5261.7 2157.73
#Mann= 7 ,-1 , 0
  4361.7    .035       0  4547.1     .16       0  4865.5     .07       0
  4943.3     .16       0  5007.2     .07       0  5030.2     .16       0
  5242.2     .07       0
Bank Sta=5007.2,5030.2
XS Rating Curve= 0 ,0
Exp/Cntr=0.3,0.1

Chan Stop Cuts=-1
Use User Specified Reach Order=0
Composite Channel Slope=5