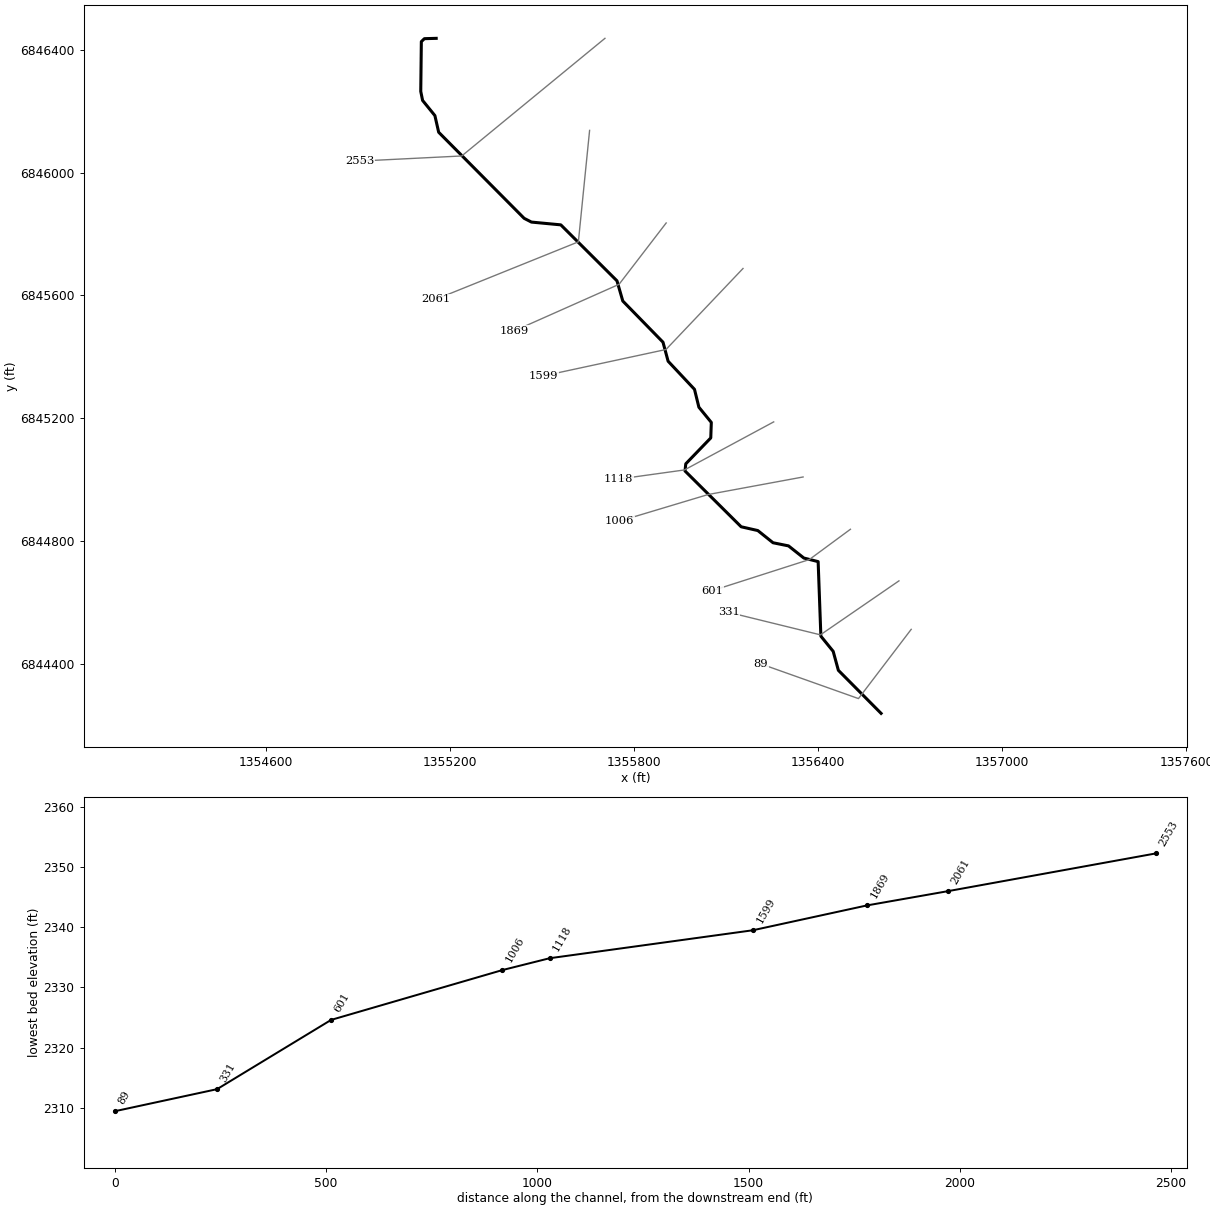
--- Long Branch Trib1.prj (project) ---

Proj Title=Long Branch Trib1 Base Level Engineering
Current Plan=p01
Default Exp/Contr=0.3,0.1
English Units
Geom File=g01
Flow File=f01
Plan File=p01
Y Axis Title=Elevation
X Axis Title(PF)=Main Channel Distance
X Axis Title(XS)=Station
BEGIN DESCRIPTION:
Long Branch Trib1
END DESCRIPTION:
DSS Export Rating Curves= 0
DSS Export Rating Curve Sorted= 0
DSS Export Volume Flow Curves= 0
DXF OffsetX= 0
DXF OffsetY= 0
DXF ScaleX= 1
DXF ScaleY= 10

--- Long Branch Trib1.p01 (plan) ---

Plan Title=Multiple Run
Short Identifier=Multiple
Geom File=g01
Flow File=f01
Subcritical Flow
K Sum by GR= 0
Std Step Tol= 0.01
Critical Tol= 0.01
Num of Std Step Trials= 20
Max Error Tol= 0.3
Flow Tol Ratio= 0.001
Split Flow NTrial= 30
Split Flow Tol= 0.02
Split Flow Ratio= 0.02
Log Output Level= 0
Friction Slope Method= 1
Unsteady Friction Slope Method= 2
Unsteady Bridges Friction Slope Method= 1
Parabolic Critical Depth
Global Vel Dist=  1 , 1 , 1
Global Log Level= 0
CheckData=True
Encroach Param= -1, 0, 0, 0
BEGIN DESCRIPTION:
Multiple Run
END DESCRIPTION:

--- Long Branch Trib1.f01 (steady flow) ---

Flow Title=Multiple
Number of Profiles=7
Profile Names=10-year,25-year,50-year,1pct_min,100-year,1pct_plu,500-year
River Rch & RM= Long Branch Trib,Reach-1,2553
      87     115     138      83     165     329     237
Boundary for River Rch & Prof#=Long Branch Trib,Reach-1,1
Up Type=0
Dn Type=3
Dn Slope=0.005
Boundary for River Rch & Prof#=Long Branch Trib,Reach-1,2
Up Type=0
Dn Type=3
Dn Slope=0.005
Boundary for River Rch & Prof#=Long Branch Trib,Reach-1,3
Up Type=0
Dn Type=3
Dn Slope=0.005
Boundary for River Rch & Prof#=Long Branch Trib,Reach-1,4
Up Type=0
Dn Type=3
Dn Slope=0.005
Boundary for River Rch & Prof#=Long Branch Trib,Reach-1,5
Up Type=0
Dn Type=3
Dn Slope=0.005
Boundary for River Rch & Prof#=Long Branch Trib,Reach-1,6
Up Type=0
Dn Type=3
Dn Slope=0.005
Boundary for River Rch & Prof#=Long Branch Trib,Reach-1,7
Up Type=0
Dn Type=3
Dn Slope=0.005

--- Long Branch Trib1.g01 (geometry) ---

Geom Title=Existing Conditions

River Reach=Long Branch Trib,Reach-1
Reach XY= 30
      1355155.00      6846438.00      1355116.51      6846436.93
      1355106.62      6846427.29      1355104.70      6846265.15
      1355110.71      6846235.65      1355150.78      6846186.25
      1355163.14      6846131.94      1355441.70      6845851.40
      1355465.48      6845839.17      1355561.17      6845830.14
      1355744.22      6845647.68      1355763.16      6845581.95
      1355894.22      6845447.68      1355910.87      6845385.72
      1355996.85      6845294.05      1356011.18      6845235.81
      1356051.69      6845186.26      1356049.88      6845135.70
      1355968.44      6845051.32      1355965.96      6845028.00
      1356148.94      6844846.14      1356203.26      6844833.81
      1356252.81      6844794.08      1356303.31      6844783.85
      1356353.21      6844744.27      1356399.83      6844732.59
      1356408.75      6844489.55      1356448.86      6844440.17
      1356465.76      6844378.31      1356605.00      6844238.00

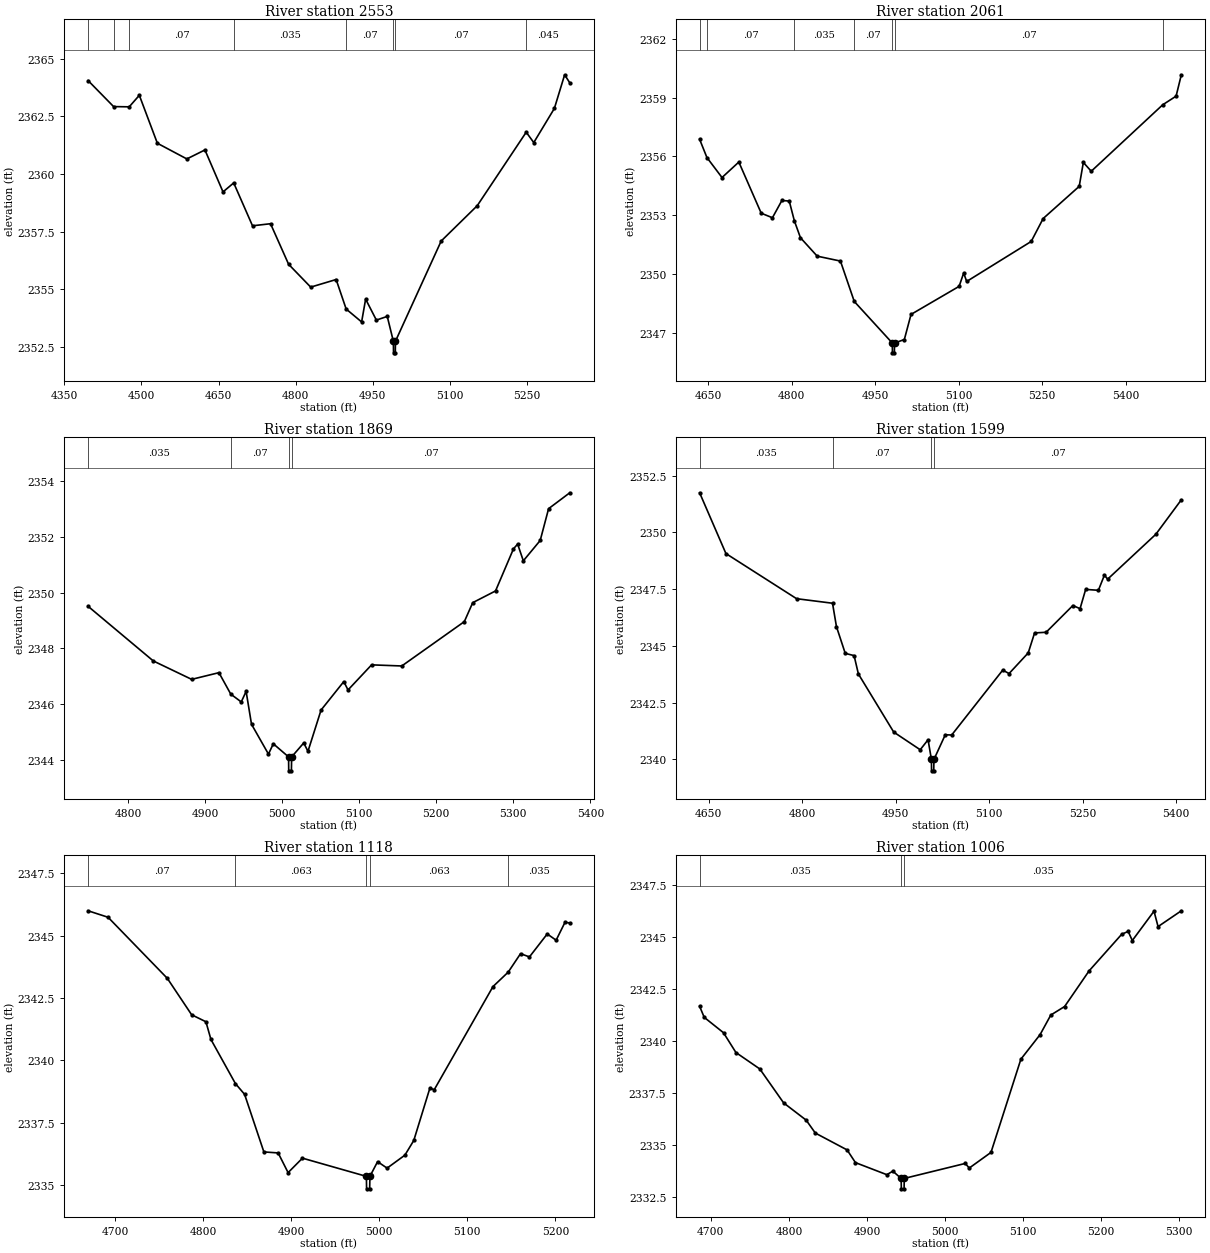
Type RM Length L Ch R = 1,2553,492,492,492
BEGIN DESCRIPTION:
Long Branch Trib1 4.0
END DESCRIPTION:
XS GIS Cut Line= 3
      1355705.03      6846438.03      1355238.30      6846054.65
      1354905.02      6846038.00
#Sta/Elev= 30
  4396.0 2364.05  4445.7 2362.92  4476.1 2362.91  4495.8 2363.41  4530.9 2361.33
  4588.3 2360.65  4623.5 2361.04  4658.7 2359.22  4679.5 2359.61  4716.1 2357.75
  4751.2 2357.84  4786.4 2356.08  4829.4 2355.09  4878.9 2355.42  4898.4 2354.14
  4928.5 2353.58  4936.3 2354.57  4957.2 2353.66  4978.4 2353.82  4990.3 2352.74
  4990.6 2352.24  4994.1 2352.24  4994.3 2352.74  5083.4 2357.09  5153.5 2358.62
  5248.9 2361.81  5263.6 2361.36  5303.7 2362.84  5323.7 2364.30  5333.7 2363.95
#Mann=8,-1,0
  4396.0   0.045       0  4445.7   0.035       0  4476.1    0.07       0
  4679.5   0.035       0  4898.4    0.07       0  4990.3    0.07       0
  4994.3    0.07       0  5248.9   0.045       0
Bank Sta=4990.3,4994.3
Exp/Cntr=0.3,0.1

Type RM Length L Ch R = 1,2061,192,192,192
BEGIN DESCRIPTION:
Long Branch Trib1 3.0
END DESCRIPTION:
XS GIS Cut Line= 3
      1355655.00      6846138.05      1355618.38      6845774.79
      1355155.01      6845588.01
#Sta/Elev= 30
  4634.9 2356.87  4648.0 2355.94  4675.1 2354.92  4705.3 2355.71  4745.5 2353.10
  4765.6 2352.87  4782.6 2353.75  4795.8 2353.72  4805.0 2352.71  4815.9 2351.85
  4846.0 2350.91  4887.7 2350.66  4912.5 2348.60  4980.8 2346.48  4981.0 2345.98
  4984.5 2345.98  4984.8 2346.48  5002.4 2346.66  5014.4 2347.94  5100.7 2349.37
  5108.9 2350.05  5114.3 2349.62  5230.1 2351.66  5251.6 2352.83  5316.3 2354.47
  5323.7 2355.69  5337.9 2355.24  5466.2 2358.63  5490.2 2359.07  5499.6 2360.16
#Mann=7,-1,0
  4634.9   0.035       0  4648.0    0.07       0  4805.0   0.035       0
  4912.5    0.07       0  4980.8    0.07       0  4984.8    0.07       0
  5466.2   0.035       0
Bank Sta=4980.8,4984.8
Exp/Cntr=0.3,0.1

Type RM Length L Ch R = 1,1869,270,270,270
BEGIN DESCRIPTION:
Long Branch Trib1 4349
END DESCRIPTION:
XS GIS Cut Line= 3
      1355904.57      6845836.30      1355751.02      6845636.35
      1355409.89      6845484.76
#Sta/Elev= 30
  4747.9 2349.51  4832.6 2347.55  4882.4 2346.89  4917.8 2347.13  4933.2 2346.36
  4946.8 2346.08  4953.1 2346.46  4960.1 2345.28  4982.1 2344.21  4988.4 2344.58
  5008.2 2344.11  5008.4 2343.61  5011.9 2343.61  5012.2 2344.11  5027.9 2344.61
  5033.4 2344.31  5050.4 2345.79  5079.9 2346.81  5085.4 2346.51  5116.0 2347.41
  5155.2 2347.37  5236.4 2348.96  5247.3 2349.64  5276.9 2350.06  5300.2 2351.57
  5305.6 2351.74  5313.0 2351.14  5334.9 2351.87  5345.8 2353.01  5373.3 2353.58
#Mann=4,-1,0
  4747.9   0.035       0  4933.2    0.07       0  5008.2    0.07       0
  5012.2    0.07       0
Bank Sta=5008.2,5012.2
Exp/Cntr=0.3,0.1

Type RM Length L Ch R = 1,1599,481,481,481
BEGIN DESCRIPTION:
Long Branch Trib1 2.0
END DESCRIPTION:
XS GIS Cut Line= 3
      1356154.97      6845687.97      1355903.97      6845423.94
      1355505.02      6845338.00
#Sta/Elev= 30
  4635.7 2351.75  4677.9 2349.07  4791.2 2347.08  4848.8 2346.88  4855.1 2345.85
  4869.2 2344.67  4883.4 2344.57  4890.3 2343.76  4946.9 2341.20  4989.4 2340.42
  5002.0 2340.86  5007.4 2339.99  5007.6 2339.49  5011.1 2339.49  5011.4 2339.99
  5029.6 2341.08  5039.9 2341.07  5121.7 2343.93  5131.9 2343.78  5162.6 2344.69
  5172.8 2345.57  5191.3 2345.60  5234.2 2346.78  5245.7 2346.64  5254.7 2347.49
  5275.1 2347.45  5284.8 2348.12  5289.9 2347.94  5367.2 2349.92  5408.1 2351.44
#Mann=4,-1,0
  4635.7   0.035       0  4848.8    0.07       0  5007.4    0.07       0
  5011.4    0.07       0
Bank Sta=5007.4,5011.4
Exp/Cntr=0.3,0.1

Type RM Length L Ch R = 1,1118,112,112,112
BEGIN DESCRIPTION:
Long Branch Trib1 1.0
END DESCRIPTION:
XS GIS Cut Line= 3
      1356254.98      6845187.99      1355963.96      6845031.33
      1355749.62      6845001.56
#Sta/Elev= 30
  4669.5 2346.00  4692.2 2345.74  4759.5 2343.29  4787.1 2341.83  4803.3 2341.55
  4809.0 2340.84  4836.8 2339.07  4847.2 2338.64  4869.1 2336.33  4885.3 2336.29
  4896.6 2335.50  4912.9 2336.08  4985.5 2335.35  4985.7 2334.85  4989.2 2334.85
  4989.5 2335.35  4998.2 2335.94  5009.0 2335.68  5029.2 2336.20  5039.3 2336.79
  5057.5 2338.88  5062.6 2338.83  5129.2 2342.96  5146.5 2343.54  5160.5 2344.28
  5170.6 2344.15  5190.8 2345.07  5200.9 2344.82  5211.0 2345.54  5216.4 2345.51
#Mann=5,-1,0
  4669.5    0.07       0  4836.8   0.063       0  4985.5   0.063       0
  4989.5   0.063       0  5146.5   0.035       0
Bank Sta=4985.5,4989.5
Exp/Cntr=0.3,0.1

Type RM Length L Ch R = 1,1006,405,405,405
BEGIN DESCRIPTION:
Long Branch Trib1 4352
END DESCRIPTION:
XS GIS Cut Line= 3
      1356350.78      6845008.44      1356041.61      6844951.33
      1355751.78      6844864.34
#Sta/Elev= 30
  4685.6 2341.65  4691.5 2341.12  4716.2 2340.38  4732.1 2339.43  4762.7 2338.64
  4793.2 2337.01  4822.1 2336.18  4833.8 2335.56  4874.5 2334.75  4885.2 2334.14
  4925.4 2333.56  4933.1 2333.73  4943.7 2333.38  4944.0 2332.88  4947.5 2332.88
  4947.7 2333.38  5025.8 2334.10  5031.0 2333.88  5058.8 2334.63  5097.1 2339.11
  5121.7 2340.29  5135.4 2341.23  5153.1 2341.64  5184.4 2343.35  5226.2 2345.11
  5234.5 2345.25  5239.8 2344.81  5267.6 2346.22  5272.8 2345.48  5302.6 2346.24
#Mann=3,-1,0
  4685.6   0.035       0  4943.7   0.035       0  4947.7   0.035       0
Bank Sta=4943.7,4947.7
Exp/Cntr=0.3,0.1

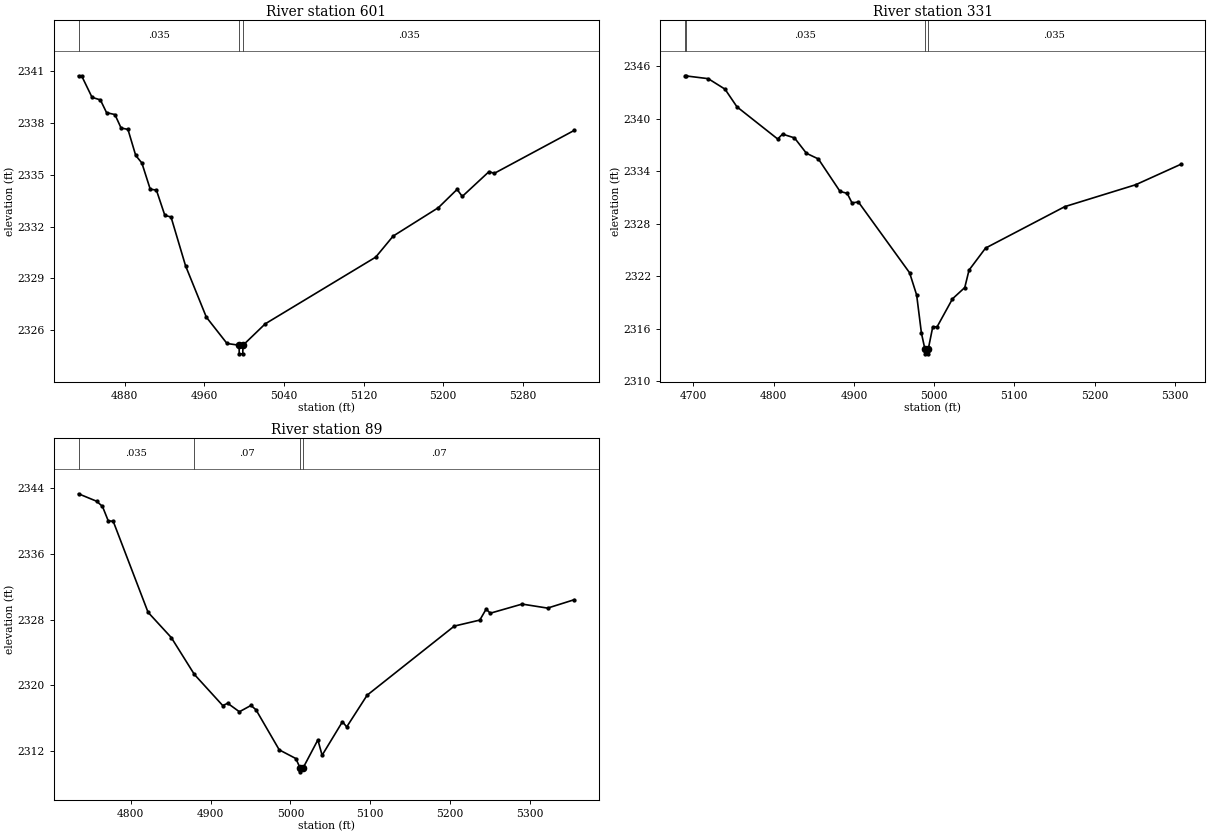
Type RM Length L Ch R = 1,601,270,270,270
BEGIN DESCRIPTION:
Long Branch Trib1 0.1
END DESCRIPTION:
XS GIS Cut Line= 3
      1356505.03      6844838.02      1356370.90      6844739.20
      1356055.02      6844638.01
#Sta/Elev= 30
  4833.4 2340.75  4836.5 2340.75  4847.0 2339.50  4855.4 2339.35  4861.6 2338.61
  4870.0 2338.50  4876.2 2337.72  4883.1 2337.64  4890.9 2336.13  4897.1 2335.69
  4905.5 2334.17  4911.7 2334.12  4920.2 2332.65  4926.4 2332.56  4941.0 2329.73
  4961.9 2326.75  4982.7 2325.22  4994.8 2325.12  4995.0 2324.62  4998.5 2324.62
  4998.8 2325.12  5021.1 2326.36  5132.2 2330.23  5149.7 2331.45  5195.2 2333.10
  5214.0 2334.16  5219.2 2333.75  5246.1 2335.19  5251.4 2335.09  5331.7 2337.58
#Mann=3,-1,0
  4833.4   0.035       0  4994.8   0.035       0  4998.8   0.035       0
Bank Sta=4994.8,4998.8
Exp/Cntr=0.3,0.1

Type RM Length L Ch R = 1,331,242,242,242
BEGIN DESCRIPTION:
Long Branch Trib1 4350
END DESCRIPTION:
XS GIS Cut Line= 3
      1356663.20      6844669.87      1356407.24      6844493.93
      1356108.80      6844567.19
#Sta/Elev= 30
  4689.4 2344.92  4690.1 2344.91  4718.4 2344.59  4739.3 2343.39  4754.2 2341.37
  4805.0 2337.69  4811.0 2338.25  4825.9 2337.82  4840.8 2336.06  4855.7 2335.41
  4882.7 2331.70  4891.6 2331.48  4897.6 2330.39  4905.6 2330.49  4969.4 2322.40
  4978.2 2319.86  4984.2 2315.48  4988.6 2313.63  4988.8 2313.13  4992.3 2313.13
  4992.6 2313.63  4998.3 2316.22  5003.7 2316.22  5022.9 2319.42  5038.2 2320.71
  5043.5 2322.70  5064.1 2325.22  5162.9 2329.96  5251.2 2332.46  5307.3 2334.79
#Mann=4,-1,0
  4689.4    0.07       0  4690.1   0.035       0  4988.6   0.035       0
  4992.6   0.035       0
Bank Sta=4988.6,4992.6
Exp/Cntr=0.3,0.1

Type RM Length L Ch R = 1,89,0,0,0
BEGIN DESCRIPTION:
Long Branch Trib1 4351
END DESCRIPTION:
XS GIS Cut Line= 3
      1356703.14      6844511.87      1356531.29      6844286.21
      1356213.58      6844399.06
#Sta/Elev= 30
  4734.5 2343.35  4757.2 2342.44  4764.5 2341.81  4771.7 2340.06  4778.0 2339.99
  4821.6 2328.91  4850.7 2325.83  4879.6 2321.34  4915.1 2317.55  4921.4 2317.82
  4936.0 2316.79  4950.5 2317.56  4956.8 2317.03  4985.9 2312.15  5006.7 2311.09
  5011.9 2309.97  5012.1 2309.47  5015.9 2309.97  5034.3 2313.36  5039.6 2311.49
  5065.1 2315.58  5070.4 2314.94  5096.0 2318.81  5205.2 2327.23  5237.1 2327.96
  5245.0 2329.29  5250.3 2328.80  5290.1 2329.91  5322.0 2329.42  5355.3 2330.44
#Mann=4,-1,0
  4734.5   0.035       0  4879.6    0.07       0  5011.9    0.07       0
  5015.9    0.07       0
Bank Sta=5011.9,5015.9
Exp/Cntr=0.3,0.1

Chan Stop Cuts=-1