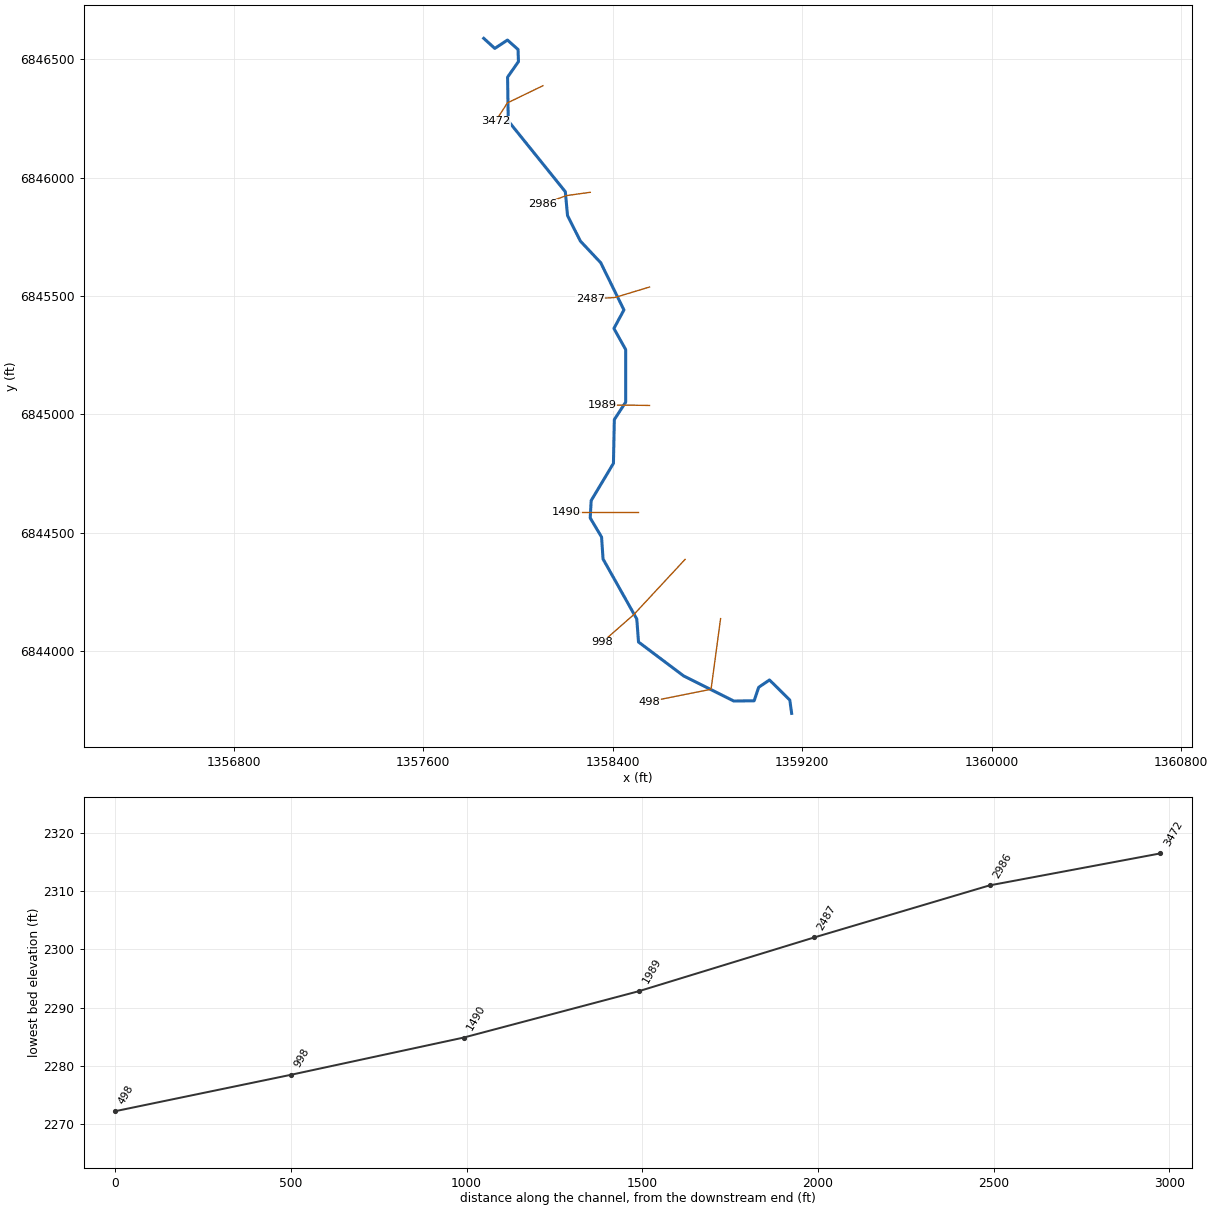
--- Long Branch Trib2.prj (project) ---

Proj Title=Long Branch Trib2 Base Level Engineering
Current Plan=p01
Default Exp/Contr=0.3,0.1
English Units
Geom File=g01
Flow File=f01
Plan File=p01
BEGIN DESCRIPTION:
Long Branch Trib2
END DESCRIPTION:

--- Long Branch Trib2.p01 (plan) ---

Plan Title=Multiple Run
Short Identifier=Multiple
Geom File=g01
Flow File=f01
Subcritical Flow
K Sum by GR= 0
Std Step Tol= 0.01
Critical Tol= 0.01
Num of Std Step Trials= 20
Max Error Tol= 0.3
Flow Tol Ratio= 0.001
Split Flow NTrial= 30
Split Flow Tol= 0.02
Split Flow Ratio= 0.02
Log Output Level= 0
Friction Slope Method= 1
Unsteady Friction Slope Method= 2
Unsteady Bridges Friction Slope Method= 1
Parabolic Critical Depth
Global Vel Dist=  1 , 1 , 1
Global Log Level= 0
CheckData=True
Encroach Param= -1, 0, 0, 0
BEGIN DESCRIPTION:
Multiple Run
END DESCRIPTION:

--- Long Branch Trib2.f01 (steady flow) ---

Flow Title=Multiple
Number of Profiles=7
Profile Names=10-year,25-year,50-year,1pct_min,100-year,1pct_plu,500-year
River Rch & RM= Long Branch Trib,Reach-1,3472
     182     255     315     195     389     776     598
Boundary for River Rch & Prof#=Long Branch Trib,Reach-1,1
Up Type=0
Dn Type=3
Dn Slope=0.005
Boundary for River Rch & Prof#=Long Branch Trib,Reach-1,2
Up Type=0
Dn Type=3
Dn Slope=0.005
Boundary for River Rch & Prof#=Long Branch Trib,Reach-1,3
Up Type=0
Dn Type=3
Dn Slope=0.005
Boundary for River Rch & Prof#=Long Branch Trib,Reach-1,4
Up Type=0
Dn Type=3
Dn Slope=0.005
Boundary for River Rch & Prof#=Long Branch Trib,Reach-1,5
Up Type=0
Dn Type=3
Dn Slope=0.005
Boundary for River Rch & Prof#=Long Branch Trib,Reach-1,6
Up Type=0
Dn Type=3
Dn Slope=0.005
Boundary for River Rch & Prof#=Long Branch Trib,Reach-1,7
Up Type=0
Dn Type=3
Dn Slope=0.005

--- Long Branch Trib2.g01 (geometry) ---

Geom Title=Existing Conditions

River Reach=Long Branch Trib,Reach-1
Reach XY= 30
      1357855.00      6846588.00      1357901.68      6846545.53
      1357955.29      6846580.71      1357999.92      6846540.84
      1358001.66      6846489.81      1357955.70      6846424.09
      1357958.54      6846239.46      1358199.46      6845940.42
      1358208.83      6845839.59      1358263.16      6845731.95
      1358349.15      6845640.29      1358446.93      6845441.31
      1358404.69      6845363.04      1358454.30      6845274.09
      1358454.32      6845051.92      1358406.38      6844978.34
      1358402.65      6844793.52      1358308.67      6844636.42
      1358304.60      6844563.00      1358352.53      6844482.43
      1358358.83      6844389.58      1358501.17      6844136.41
      1358508.52      6844039.28      1358698.95      6843896.16
      1358910.64      6843790.22      1358996.66      6843791.03
      1359015.90      6843848.12      1359061.53      6843879.12
      1359147.24      6843794.27      1359155.00      6843738.00

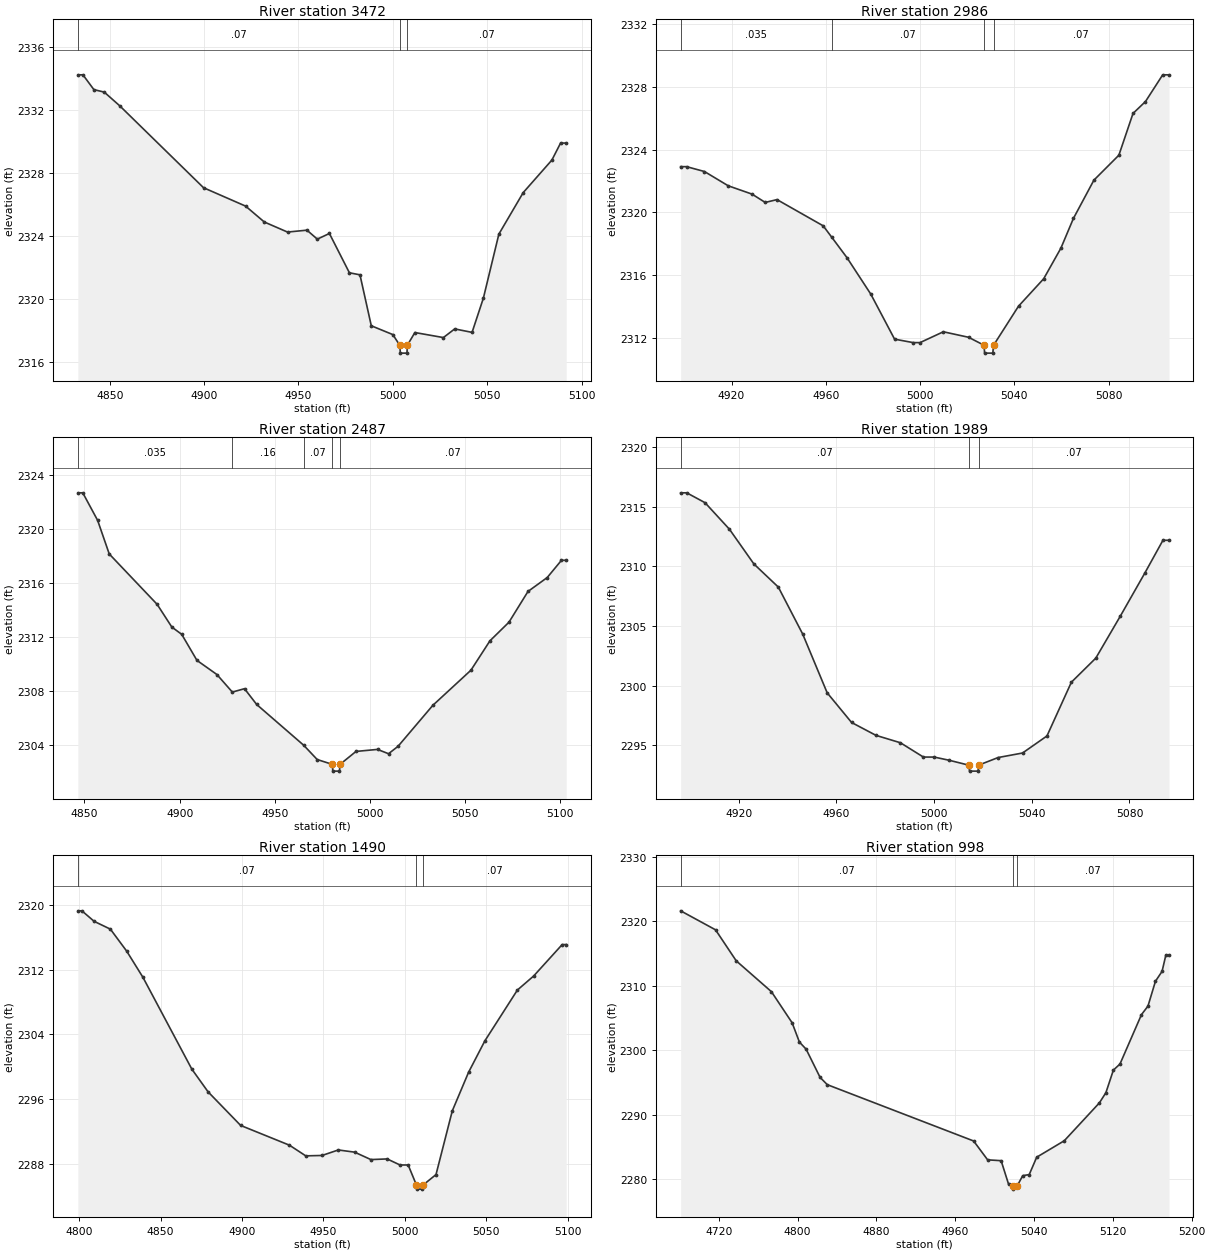
Type RM Length L Ch R = 1,3472,486,486,486
BEGIN DESCRIPTION:
Long Branch Trib2 6.0
END DESCRIPTION:
XS GIS Cut Line= 3
      1358104.97      6846387.99      1357954.78      6846315.20
      1357904.98      6846237.97
#Sta/Elev= 30
  4833.1 2334.25  4835.8 2334.25  4841.6 2333.31  4847.1 2333.15  4855.3 2332.28
  4899.7 2327.07  4922.0 2325.90  4931.9 2324.89  4944.2 2324.25  4954.5 2324.37
  4960.0 2323.80  4966.4 2324.16  4977.0 2321.66  4982.6 2321.53  4988.6 2318.29
  5000.0 2317.73  5003.7 2317.05  5004.0 2316.55  5007.5 2316.55  5007.7 2317.05
  5011.7 2317.86  5026.8 2317.54  5032.8 2318.09  5042.0 2317.87  5048.0 2320.05
  5056.2 2324.12  5069.1 2326.76  5084.3 2328.83  5088.9 2329.91  5091.9 2329.91
#Mann=3,-1,0
  4833.1    0.07       0  5003.7    0.07       0  5007.7    0.07       0
Bank Sta=5003.7,5007.7
Exp/Cntr=0.3,0.1

Type RM Length L Ch R = 1,2986,499,499,499
BEGIN DESCRIPTION:
Long Branch Trib2 5.0
END DESCRIPTION:
XS GIS Cut Line= 3
      1358304.97      6845938.00      1358204.33      6845924.08
      1358104.98      6845887.99
#Sta/Elev= 30
  4898.4 2322.92  4900.9 2322.92  4908.5 2322.61  4918.6 2321.70  4928.7 2321.17
  4934.3 2320.64  4939.3 2320.82  4958.9 2319.15  4962.5 2318.43  4969.0 2317.12
  4979.1 2314.80  4989.2 2311.93  4997.1 2311.71  5000.0 2311.71  5009.9 2312.40
  5020.6 2312.05  5027.2 2311.54  5027.4 2311.04  5030.9 2311.04  5031.2 2311.54
  5041.8 2314.03  5052.5 2315.78  5059.8 2317.73  5065.1 2319.62  5073.8 2322.06
  5084.4 2323.65  5090.4 2326.31  5095.7 2327.07  5103.0 2328.77  5105.7 2328.77
#Mann=4,-1,0
  4898.4   0.035       0  4962.5    0.07       0  5027.2    0.07       0
  5031.2    0.07       0
Bank Sta=5027.2,5031.2
Exp/Cntr=0.3,0.1

Type RM Length L Ch R = 1,2487,498,498,498
BEGIN DESCRIPTION:
Long Branch Trib2 4.0
END DESCRIPTION:
XS GIS Cut Line= 3
      1358554.97      6845537.99      1358408.02      6845493.63
      1358304.97      6845488.00
#Sta/Elev= 30
  4846.5 2322.70  4849.1 2322.70  4856.9 2320.66  4863.0 2318.17  4888.2 2314.43
  4895.9 2312.75  4901.1 2312.21  4909.1 2310.28  4919.6 2309.23  4927.7 2307.93
  4934.1 2308.18  4940.5 2307.01  4965.2 2303.99  4972.3 2302.93  4980.3 2302.57
  4980.5 2302.07  4984.0 2302.07  4984.3 2302.57  4992.7 2303.53  5004.0 2303.68
  5009.8 2303.36  5014.8 2303.91  5033.1 2306.95  5053.1 2309.55  5063.1 2311.73
  5073.1 2313.11  5083.1 2315.39  5093.2 2316.42  5100.7 2317.70  5103.2 2317.70
#Mann=5,-1,0
  4846.5   0.035       0  4927.7    0.16       0  4965.2    0.07       0
  4980.3    0.07       0  4984.3    0.07       0
Bank Sta=4980.3,4984.3
Exp/Cntr=0.3,0.1

Type RM Length L Ch R = 1,1989,499,499,499
BEGIN DESCRIPTION:
Long Branch Trib2 3.0
END DESCRIPTION:
XS GIS Cut Line= 3
      1358555.01      6845038.00      1358451.22      6845039.57
      1358355.03      6845038.00
#Sta/Elev= 27
  4896.2 2316.18  4898.7 2316.18  4906.2 2315.35  4916.2 2313.12  4926.2 2310.21
  4936.2 2308.27  4946.2 2304.32  4956.2 2299.40  4966.2 2296.91  4976.2 2295.83
  4986.2 2295.21  4995.6 2294.01  5000.0 2294.01  5006.2 2293.74  5014.2 2293.33
  5014.5 2292.83  5018.0 2292.83  5018.2 2293.33  5026.2 2293.97  5036.2 2294.35
  5046.2 2295.78  5056.2 2300.29  5066.2 2302.31  5076.2 2305.82  5086.2 2309.42
  5093.7 2312.20  5096.2 2312.20
#Mann=3,-1,0
  4896.2    0.07       0  5014.2    0.07       0  5018.2    0.07       0
Bank Sta=5014.2,5018.2
Exp/Cntr=0.3,0.1

Type RM Length L Ch R = 1,1490,492,492,492
BEGIN DESCRIPTION:
Long Branch Trib2 2.0
END DESCRIPTION:
XS GIS Cut Line= 3
      1358504.98      6844588.00      1358304.18      6844588.00
      1358204.98      6844588.00
#Sta/Elev= 30
  4799.2 2319.30  4801.7 2319.30  4809.2 2318.00  4819.2 2317.03  4829.2 2314.31
  4839.2 2311.06  4869.2 2299.70  4879.2 2296.88  4899.2 2292.72  4929.2 2290.27
  4939.2 2288.95  4949.2 2289.00  4959.2 2289.68  4969.2 2289.41  4979.2 2288.49
  4989.2 2288.57  4997.1 2287.82  5002.1 2287.82  5007.2 2285.33  5007.4 2284.83
  5010.9 2284.83  5011.2 2285.33  5019.2 2286.63  5029.2 2294.52  5039.2 2299.30
  5049.2 2303.19  5069.2 2309.49  5079.2 2311.23  5096.7 2315.12  5099.2 2315.12
#Mann=3,-1,0
  4799.2    0.07       0  5007.2    0.07       0  5011.2    0.07       0
Bank Sta=5007.2,5011.2
Exp/Cntr=0.3,0.1

Type RM Length L Ch R = 1,998,500,500,500
BEGIN DESCRIPTION:
Long Branch Trib2 1.0
END DESCRIPTION:
XS GIS Cut Line= 3
      1358705.01      6844388.01      1358488.16      6844154.60
      1358355.00      6844038.00
#Sta/Elev= 30
  4681.4 2321.65  4716.8 2318.70  4737.8 2313.88  4773.5 2309.09  4794.5 2304.26
  4801.9 2301.26  4808.7 2300.16  4822.9 2295.77  4830.2 2294.64  4978.7 2285.89
  4992.9 2282.96  5006.6 2282.83  5014.2 2279.15  5018.9 2278.91  5019.1 2278.41
  5022.9 2278.91  5028.5 2280.50  5035.1 2280.67  5042.7 2283.37  5070.7 2285.93
  5106.3 2291.81  5112.9 2293.39  5120.5 2296.90  5127.2 2297.85  5149.0 2305.52
  5155.6 2306.85  5163.2 2310.71  5169.9 2312.24  5173.7 2314.74  5177.0 2314.74
#Mann=3,-1,0
  4681.4    0.07       0  5018.9    0.07       0  5022.9    0.07       0
Bank Sta=5018.9,5022.9
Exp/Cntr=0.3,0.1

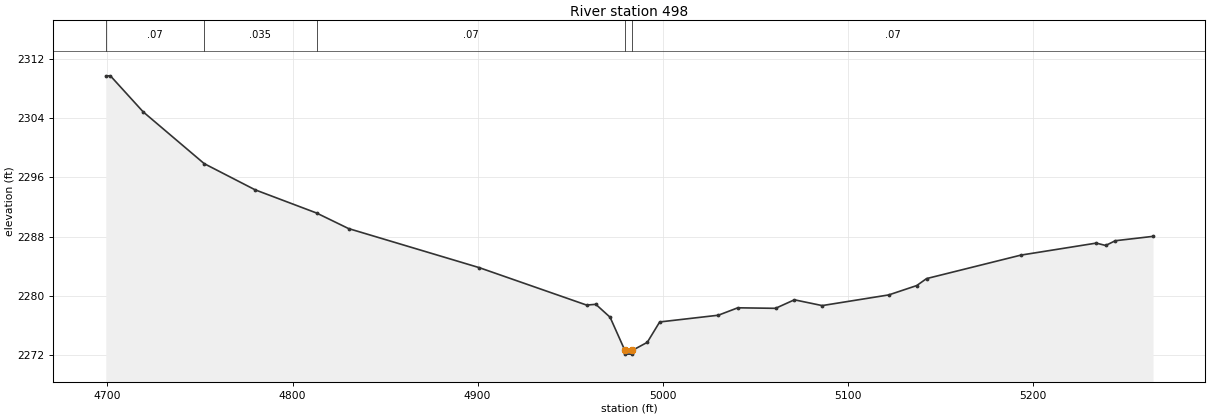
Type RM Length L Ch R = 1,498,0,0,0
BEGIN DESCRIPTION:
Long Branch Trib2 0.1
END DESCRIPTION:
XS GIS Cut Line= 3
      1358855.00      6844138.02      1358814.84      6843839.81
      1358554.96      6843787.99
#Sta/Elev= 30
  4699.1 2309.69  4701.6 2309.69  4719.3 2304.83  4752.3 2297.84  4779.8 2294.31
  4813.0 2291.18  4830.3 2289.08  4900.9 2283.81  4958.9 2278.76  4963.9 2278.86
  4971.6 2277.12  4979.6 2272.64  4979.9 2272.14  4983.4 2272.14  4983.6 2272.64
  4991.7 2273.73  4998.4 2276.48  5030.1 2277.39  5040.6 2278.39  5061.0 2278.32
  5071.2 2279.47  5086.2 2278.69  5122.2 2280.13  5137.3 2281.39  5142.6 2282.33
  5193.6 2285.50  5234.3 2287.12  5239.4 2286.80  5244.6 2287.44  5265.0 2288.03
#Mann=5,-1,0
  4699.1    0.07       0  4752.3   0.035       0  4813.0    0.07       0
  4979.6    0.07       0  4983.6    0.07       0
Bank Sta=4979.6,4983.6
Exp/Cntr=0.3,0.1

Chan Stop Cuts=-1