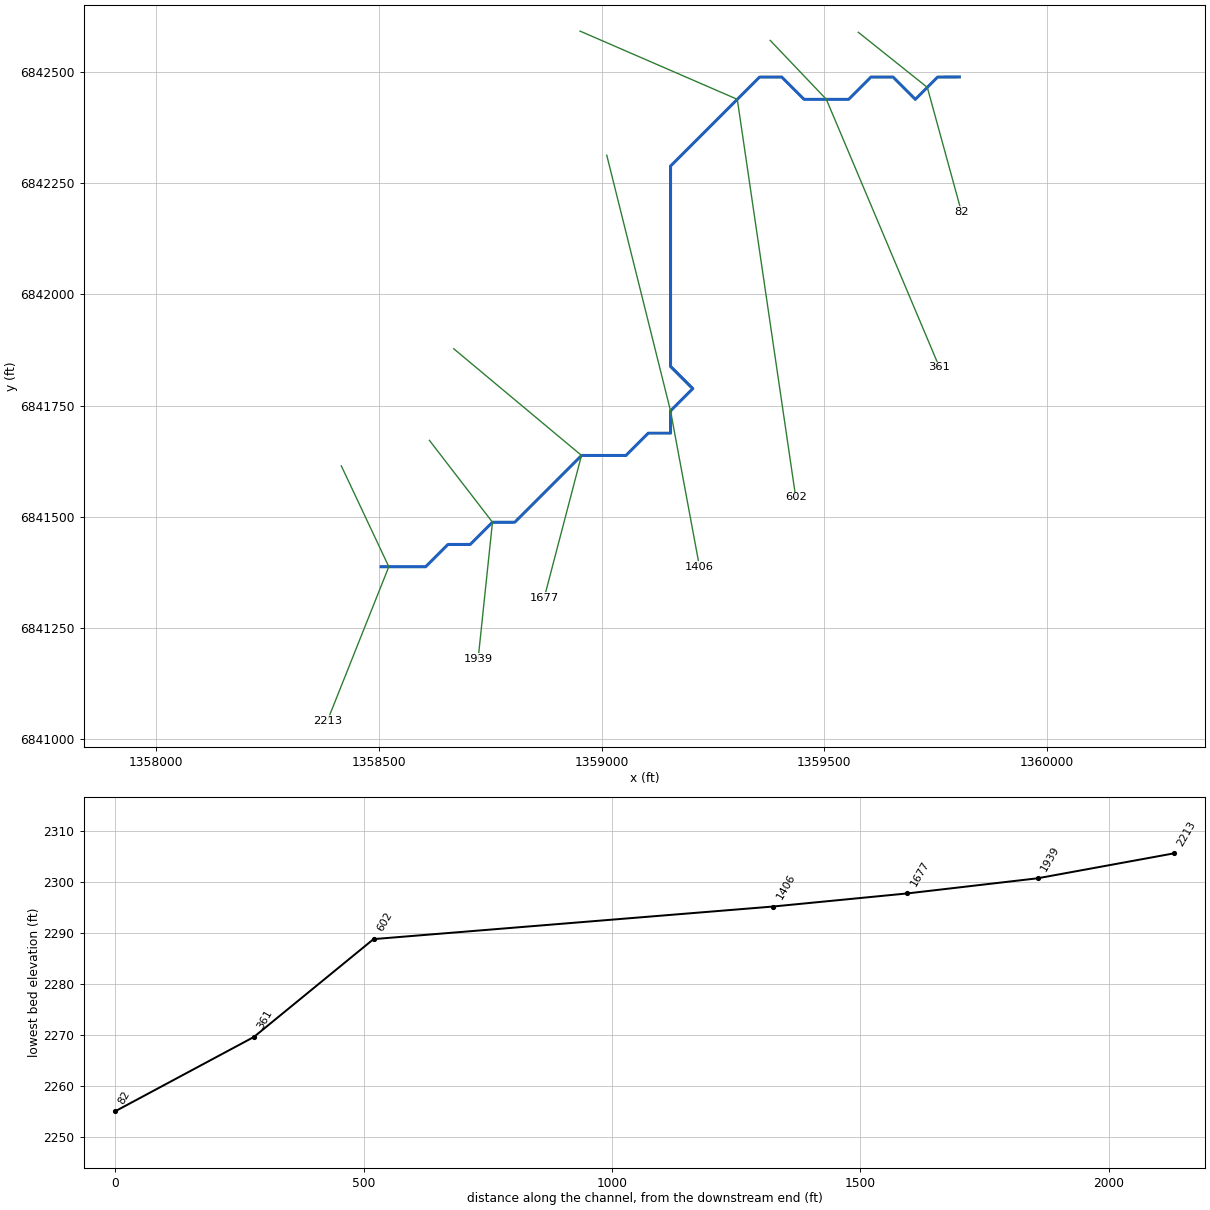
--- Long Branch Trib2_5.prj (project) ---

Proj Title=Long Branch Trib2_5 Base Level Engineering
Current Plan=p01
Default Exp/Contr=0.3,0.1
English Units
Geom File=g01
Flow File=f01
Plan File=p01
Y Axis Title=Elevation
X Axis Title(PF)=Main Channel Distance
X Axis Title(XS)=Station
BEGIN DESCRIPTION:
Long Branch Trib2_5
END DESCRIPTION:
DSS Export Rating Curves= 0
DSS Export Rating Curve Sorted= 0
DSS Export Volume Flow Curves= 0
DXF OffsetX= 0
DXF OffsetY= 0
DXF ScaleX= 1
DXF ScaleY= 10

--- Long Branch Trib2_5.p01 (plan) ---

Plan Title=Multiple Run
Short Identifier=Multiple
Geom File=g01
Flow File=f01
Subcritical Flow
K Sum by GR= 0
Std Step Tol= 0.01
Critical Tol= 0.01
Num of Std Step Trials= 20
Max Error Tol= 0.3
Flow Tol Ratio= 0.001
Split Flow NTrial= 30
Split Flow Tol= 0.02
Split Flow Ratio= 0.02
Log Output Level= 0
Friction Slope Method= 1
Unsteady Friction Slope Method= 2
Unsteady Bridges Friction Slope Method= 1
Parabolic Critical Depth
Global Vel Dist=  1 , 1 , 1
Global Log Level= 0
CheckData=True
Encroach Param= -1, 0, 0, 0
BEGIN DESCRIPTION:
Multiple Run
END DESCRIPTION:

--- Long Branch Trib2_5.f01 (steady flow) ---

Flow Title=Multiple
Number of Profiles=7
Profile Names=10-year,25-year,50-year,1pct_min,100-year,1pct_plu,500-year
River Rch & RM= Long Branch Trib,Reach-1,2213
      46      58      66      38      76     151      99
Boundary for River Rch & Prof#=Long Branch Trib,Reach-1,1
Up Type=0
Dn Type=3
Dn Slope=0.005
Boundary for River Rch & Prof#=Long Branch Trib,Reach-1,2
Up Type=0
Dn Type=3
Dn Slope=0.005
Boundary for River Rch & Prof#=Long Branch Trib,Reach-1,3
Up Type=0
Dn Type=3
Dn Slope=0.005
Boundary for River Rch & Prof#=Long Branch Trib,Reach-1,4
Up Type=0
Dn Type=3
Dn Slope=0.005
Boundary for River Rch & Prof#=Long Branch Trib,Reach-1,5
Up Type=0
Dn Type=3
Dn Slope=0.005
Boundary for River Rch & Prof#=Long Branch Trib,Reach-1,6
Up Type=0
Dn Type=3
Dn Slope=0.005
Boundary for River Rch & Prof#=Long Branch Trib,Reach-1,7
Up Type=0
Dn Type=3
Dn Slope=0.005

--- Long Branch Trib2_5.g01 (geometry) ---

Geom Title=Existing Conditions

River Reach=Long Branch Trib,Reach-1
Reach XY= 23
      1358505.00      6841388.00      1358605.00      6841388.00
      1358655.00      6841438.00      1358705.00      6841438.00
      1358755.00      6841488.00      1358805.00      6841488.00
      1358955.00      6841638.00      1359055.00      6841638.00
      1359105.00      6841688.00      1359155.00      6841688.00
      1359155.00      6841738.00      1359205.00      6841788.00
      1359155.00      6841838.00      1359155.00      6842288.00
      1359355.00      6842488.00      1359405.00      6842488.00
      1359455.00      6842438.00      1359555.00      6842438.00
      1359605.00      6842488.00      1359655.00      6842488.00
      1359705.00      6842438.00      1359755.00      6842488.00
      1359803.93      6842488.24

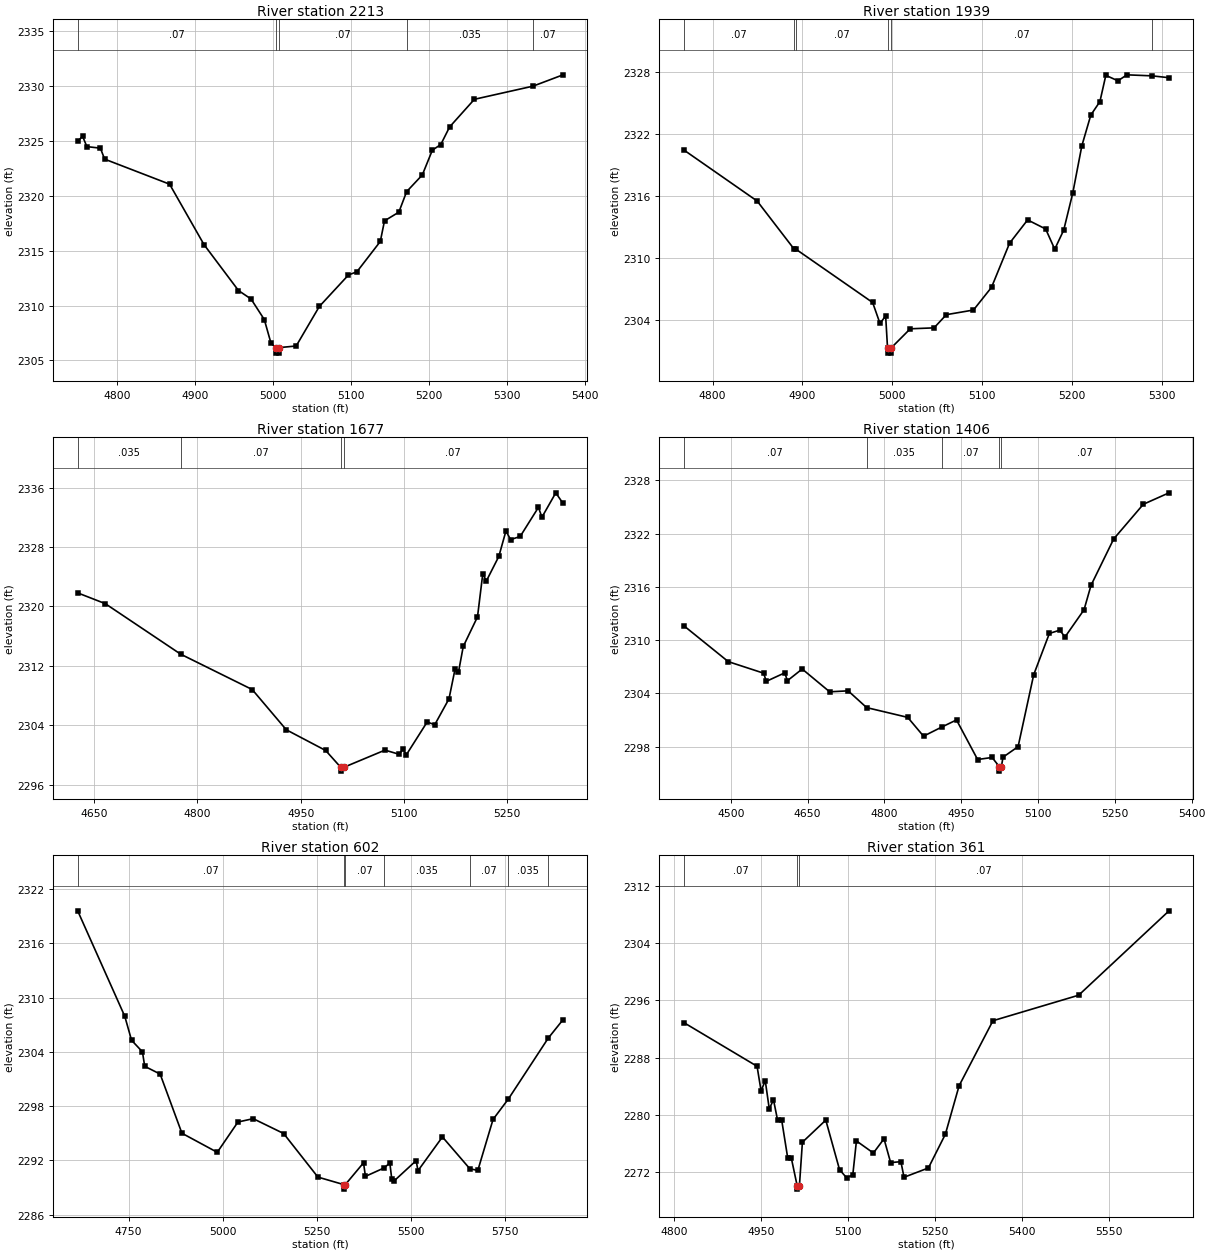
Type RM Length L Ch R = 1,2213,274,274,274
BEGIN DESCRIPTION:
Long Branch Trib2_5 4214
END DESCRIPTION:
XS GIS Cut Line= 3
      1358415.38      6841614.61      1358522.14      6841388.00
      1358384.37      6841042.35
#Sta/Elev= 30
  4749.5 2324.97  4755.8 2325.42  4761.3 2324.48  4778.6 2324.34  4784.1 2323.34
  4867.4 2321.06  4911.6 2315.55  4955.8 2311.37  4971.9 2310.60  4988.9 2308.73
  4997.5 2306.57  5003.6 2306.17  5003.8 2305.67  5007.3 2305.67  5007.6 2306.17
  5029.8 2306.32  5059.5 2309.92  5096.9 2312.79  5107.7 2313.08  5137.7 2315.84
  5143.1 2317.72  5161.5 2318.51  5171.5 2320.38  5191.6 2321.90  5204.5 2324.16
  5215.3 2324.67  5226.6 2326.27  5258.4 2328.79  5333.7 2329.99  5372.1 2331.02
#Mann=5,-1,0
  4749.5    0.07       0  5003.6    0.07       0  5007.6    0.07       0
  5171.5   0.035       0  5333.7    0.07       0
Bank Sta=5003.6,5007.6
Exp/Cntr=0.3,0.1

Type RM Length L Ch R = 1,1939,262,262,262
BEGIN DESCRIPTION:
Long Branch Trib2_5 4213
END DESCRIPTION:
XS GIS Cut Line= 3
      1358613.28      6841671.94      1358755.00      6841488.00
      1358722.83      6841181.38
#Sta/Elev= 30
  4767.8 2320.49  4849.6 2315.53  4890.3 2310.92  4892.4 2310.88  4978.2 2305.69
  4986.4 2303.66  4992.7 2304.39  4994.8 2301.28  4995.1 2300.78  4998.6 2300.78
  4998.8 2301.28  5020.1 2303.14  5046.6 2303.23  5060.3 2304.51  5090.5 2304.96
  5110.6 2307.16  5130.7 2311.44  5150.8 2313.70  5170.9 2312.82  5181.0 2310.86
  5191.0 2312.71  5201.1 2316.31  5211.2 2320.89  5221.2 2323.87  5231.3 2325.17
  5237.9 2327.72  5251.4 2327.19  5261.4 2327.77  5289.5 2327.67  5308.3 2327.49
#Mann=6,-1,0
  4767.8    0.07       0  4890.3   0.035       0  4892.4    0.07       0
  4994.8    0.07       0  4998.8    0.07       0  5289.5   0.035       0
Bank Sta=4994.8,4998.8
Exp/Cntr=0.3,0.1

Type RM Length L Ch R = 1,1677,271,271,271
BEGIN DESCRIPTION:
Long Branch Trib2_5 4211
END DESCRIPTION:
XS GIS Cut Line= 3
      1358667.99      6841877.64      1358955.00      6841638.00
      1358871.11      6841317.81
#Sta/Elev= 30
  4626.1 2321.82  4666.2 2320.37  4775.6 2313.57  4879.6 2308.80  4929.1 2303.38
  4986.3 2300.59  5008.3 2298.31  5008.6 2297.81  5012.3 2298.31  5072.4 2300.64
  5093.0 2300.08  5098.4 2300.74  5103.6 2300.03  5133.7 2304.43  5144.7 2304.06
  5165.4 2307.55  5174.1 2311.51  5179.2 2311.15  5186.1 2314.60  5206.8 2318.59
  5214.5 2324.42  5219.6 2323.41  5237.8 2326.74  5248.1 2330.16  5254.9 2329.00
  5268.8 2329.42  5295.3 2333.34  5300.4 2332.02  5320.5 2335.30  5331.0 2333.88
#Mann=4,-1,0
  4626.1   0.035       0  4775.6    0.07       0  5008.3    0.07       0
  5012.3    0.07       0
Bank Sta=5008.3,5012.3
Exp/Cntr=0.3,0.1

Type RM Length L Ch R = 1,1406,804,804,804
BEGIN DESCRIPTION:
Long Branch Trib2_5 4210
END DESCRIPTION:
XS GIS Cut Line= 3
      1359011.73      6842312.51      1359155.00      6841738.00
      1359220.03      6841388.19
#Sta/Elev= 30
  4407.9 2311.63  4495.0 2307.57  4564.0 2306.27  4569.2 2305.35  4605.3 2306.31
  4610.4 2305.42  4639.3 2306.74  4693.0 2304.17  4729.1 2304.28  4765.2 2302.39
  4845.4 2301.29  4876.3 2299.17  4912.3 2300.21  4940.7 2301.00  4981.9 2296.54
  5010.2 2296.77  5024.4 2295.73  5024.6 2295.23  5028.4 2295.73  5031.5 2296.80
  5061.0 2297.99  5091.5 2306.10  5122.1 2310.75  5142.4 2311.12  5152.6 2310.35
  5189.8 2313.42  5203.4 2316.17  5247.7 2321.40  5305.6 2325.31  5355.8 2326.60
#Mann=5,-1,0
  4407.9    0.07       0  4765.2   0.035       0  4912.3    0.07       0
  5024.4    0.07       0  5028.4    0.07       0
Bank Sta=5024.4,5028.4
Exp/Cntr=0.3,0.1

Type RM Length L Ch R = 1,602,241,241,241
BEGIN DESCRIPTION:
Long Branch Trib2_5 4212
END DESCRIPTION:
XS GIS Cut Line= 3
      1358951.80      6842591.21      1359305.00      6842438.00
      1359436.21      6841544.28
#Sta/Elev= 30
  4615.0 2319.60  4740.0 2307.94  4758.0 2305.29  4786.9 2304.01  4792.9 2302.41
  4833.9 2301.55  4891.7 2295.01  4985.5 2292.90  5040.4 2296.25  5080.9 2296.62
  5161.7 2294.98  5252.7 2290.16  5321.4 2289.33  5321.7 2288.83  5325.4 2289.33
  5373.8 2291.74  5378.8 2290.24  5428.7 2291.18  5443.6 2291.73  5448.6 2289.99
  5454.8 2289.73  5513.4 2291.98  5518.4 2290.87  5583.2 2294.60  5656.0 2291.08
  5677.2 2290.90  5717.6 2296.54  5758.5 2298.81  5864.0 2305.52  5903.3 2307.56
#Mann=7,-1,0
  4615.0    0.07       0  5321.4    0.07       0  5325.4    0.07       0
  5428.7   0.035       0  5656.0    0.07       0  5758.5   0.035       0
  5864.0    0.07       0
Bank Sta=5321.4,5325.4
Exp/Cntr=0.3,0.1

Type RM Length L Ch R = 1,361,279,279,279
BEGIN DESCRIPTION:
Long Branch Trib2_5 4209
END DESCRIPTION:
XS GIS Cut Line= 3
      1359378.92      6842570.36      1359505.00      6842438.00
      1359759.10      6841836.03
#Sta/Elev= 30
  4817.2 2292.90  4943.6 2286.78  4950.5 2283.34  4957.7 2284.77  4964.6 2280.83
  4971.9 2282.08  4978.8 2279.31  4986.0 2279.26  4996.5 2273.91  5002.7 2273.91
  5012.6 2270.10  5012.8 2269.60  5016.6 2270.10  5021.7 2276.16  5062.0 2279.25
  5085.7 2272.32  5097.7 2271.20  5108.5 2271.57  5114.8 2276.34  5144.0 2274.65
  5162.3 2276.64  5173.7 2273.31  5191.4 2273.44  5196.8 2271.26  5238.8 2272.56
  5268.0 2277.27  5291.7 2284.06  5350.0 2293.15  5497.7 2296.72  5653.4 2308.52
#Mann=3,-1,0
  4817.2    0.07       0  5012.6    0.07       0  5016.6    0.07       0
Bank Sta=5012.6,5016.6
Exp/Cntr=0.3,0.1

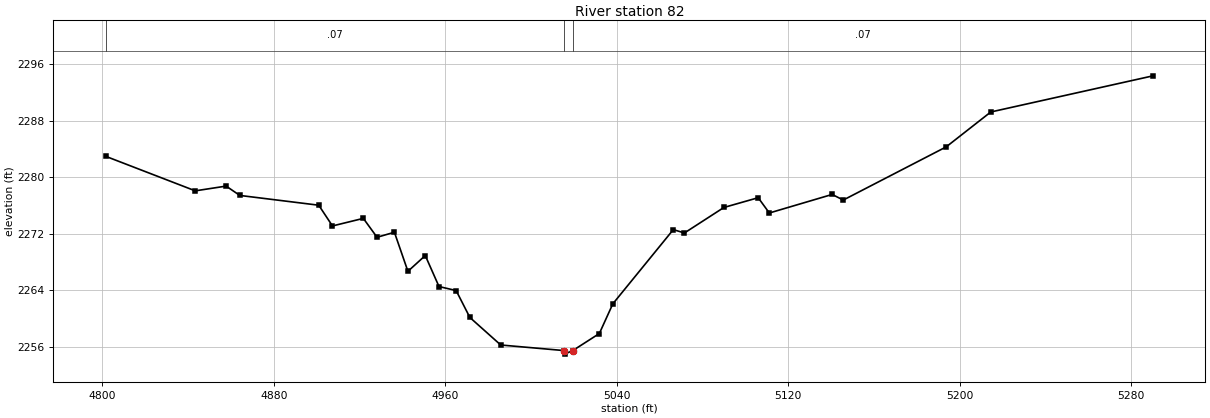
Type RM Length L Ch R = 1,82,0,0,0
BEGIN DESCRIPTION:
Long Branch Trib2_5 4208
END DESCRIPTION:
XS GIS Cut Line= 3
      1359576.79      6842588.62      1359731.84      6842464.84
      1359808.59      6842184.97
#Sta/Elev= 30
  4801.6 2282.96  4843.4 2278.08  4857.8 2278.75  4864.2 2277.43  4901.0 2276.05
  4907.4 2273.12  4921.8 2274.19  4928.2 2271.52  4936.3 2272.23  4942.6 2266.71
  4950.7 2268.94  4957.1 2264.56  4965.1 2263.99  4971.5 2260.19  4985.9 2256.30
  5015.5 2255.51  5015.7 2255.01  5019.5 2255.51  5031.9 2257.92  5038.2 2262.12
  5066.4 2272.60  5071.6 2272.13  5090.0 2275.73  5106.0 2277.11  5111.2 2274.95
  5140.5 2277.57  5145.7 2276.78  5193.7 2284.29  5214.5 2289.22  5290.2 2294.33
#Mann=3,-1,0
  4801.6    0.07       0  5015.5    0.07       0  5019.5    0.07       0
Bank Sta=5015.5,5019.5
Exp/Cntr=0.3,0.1

Chan Stop Cuts=-1