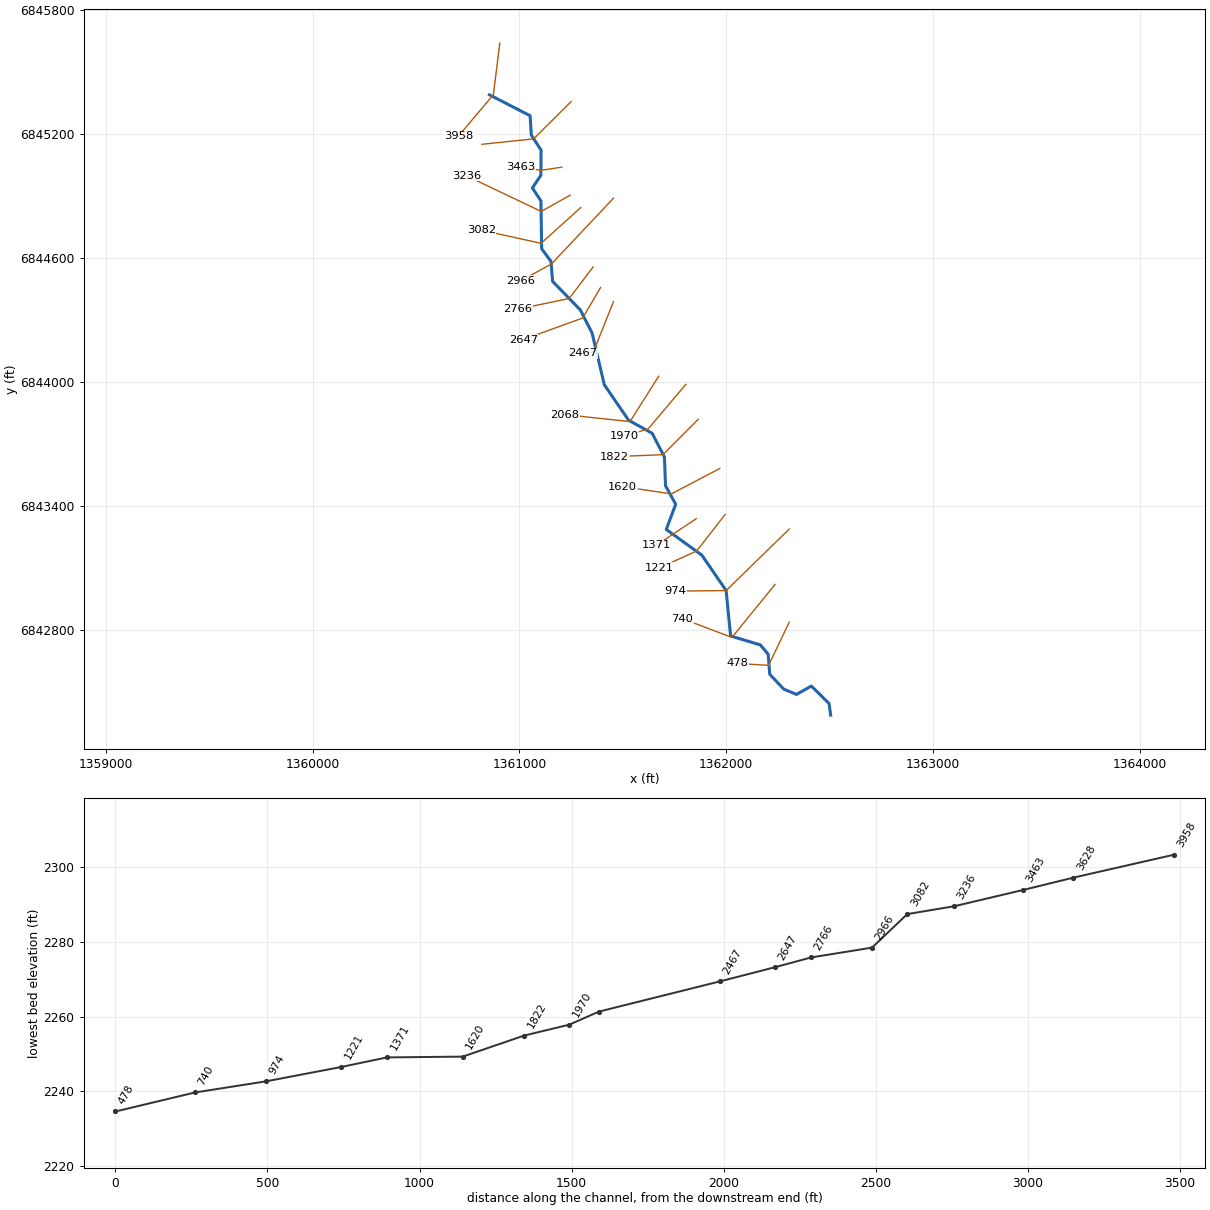
--- Long Branch Trib3.prj (project) ---

Proj Title=Long Branch Trib3 Base Level Engineering
Current Plan=p01
Default Exp/Contr=0.3,0.1
English Units
Geom File=g01
Flow File=f01
Plan File=p01
Y Axis Title=Elevation
X Axis Title(PF)=Main Channel Distance
X Axis Title(XS)=Station
BEGIN DESCRIPTION:
Long Branch Trib3
END DESCRIPTION:
DSS Export Rating Curves= 0
DSS Export Rating Curve Sorted= 0
DSS Export Volume Flow Curves= 0
DXF OffsetX= 0
DXF OffsetY= 0
DXF ScaleX= 1
DXF ScaleY= 10

--- Long Branch Trib3.p01 (plan) ---

Plan Title=Multiple Run
Short Identifier=Multiple
Geom File=g01
Flow File=f01
Subcritical Flow
K Sum by GR= 0
Std Step Tol= 0.01
Critical Tol= 0.01
Num of Std Step Trials= 20
Max Error Tol= 0.3
Flow Tol Ratio= 0.001
Split Flow NTrial= 30
Split Flow Tol= 0.02
Split Flow Ratio= 0.02
Log Output Level= 0
Friction Slope Method= 1
Unsteady Friction Slope Method= 2
Unsteady Bridges Friction Slope Method= 1
Parabolic Critical Depth
Global Vel Dist=  1 , 1 , 1
Global Log Level= 0
CheckData=True
Encroach Param= -1, 0, 0, 0
BEGIN DESCRIPTION:
Multiple Run
END DESCRIPTION:

--- Long Branch Trib3.f01 (steady flow) ---

Flow Title=Multiple
Number of Profiles=7
Profile Names=10-year,25-year,50-year,1pct_min,100-year,1pct_plu,500-year
River Rch & RM= Long Branch Trib,Reach-1,3958
     113     153     186     113     226     450     334
Boundary for River Rch & Prof#=Long Branch Trib,Reach-1,1
Up Type=0
Dn Type=3
Dn Slope=0.005
Boundary for River Rch & Prof#=Long Branch Trib,Reach-1,2
Up Type=0
Dn Type=3
Dn Slope=0.005
Boundary for River Rch & Prof#=Long Branch Trib,Reach-1,3
Up Type=0
Dn Type=3
Dn Slope=0.005
Boundary for River Rch & Prof#=Long Branch Trib,Reach-1,4
Up Type=0
Dn Type=3
Dn Slope=0.005
Boundary for River Rch & Prof#=Long Branch Trib,Reach-1,5
Up Type=0
Dn Type=3
Dn Slope=0.005
Boundary for River Rch & Prof#=Long Branch Trib,Reach-1,6
Up Type=0
Dn Type=3
Dn Slope=0.005
Boundary for River Rch & Prof#=Long Branch Trib,Reach-1,7
Up Type=0
Dn Type=3
Dn Slope=0.005

--- Long Branch Trib3.g01 (geometry) ---

Geom Title=Existing Conditions

River Reach=Long Branch Trib,Reach-1
Reach XY= 30
      1360855.00      6845388.00      1361051.48      6845286.72
      1361057.47      6845193.57      1361104.81      6845119.72
      1361103.63      6844998.44      1361062.56      6844938.00
      1361104.17      6844874.14      1361107.38      6844643.53
      1361152.53      6844582.43      1361160.52      6844485.57
      1361294.24      6844347.68      1361351.18      6844236.42
      1361410.54      6843985.58      1361527.87      6843814.17
      1361641.52      6843751.56      1361701.24      6843636.44
      1361706.39      6843497.66      1361755.66      6843407.84
      1361709.99      6843286.00      1361882.14      6843161.84
      1361999.53      6842990.45      1362021.24      6842770.78
      1362165.16      6842727.64      1362202.93      6842682.31
      1362210.52      6842585.56      1362278.11      6842514.02
      1362339.64      6842488.17      1362411.74      6842528.88
      1362497.24      6842444.27      1362505.00      6842388.00

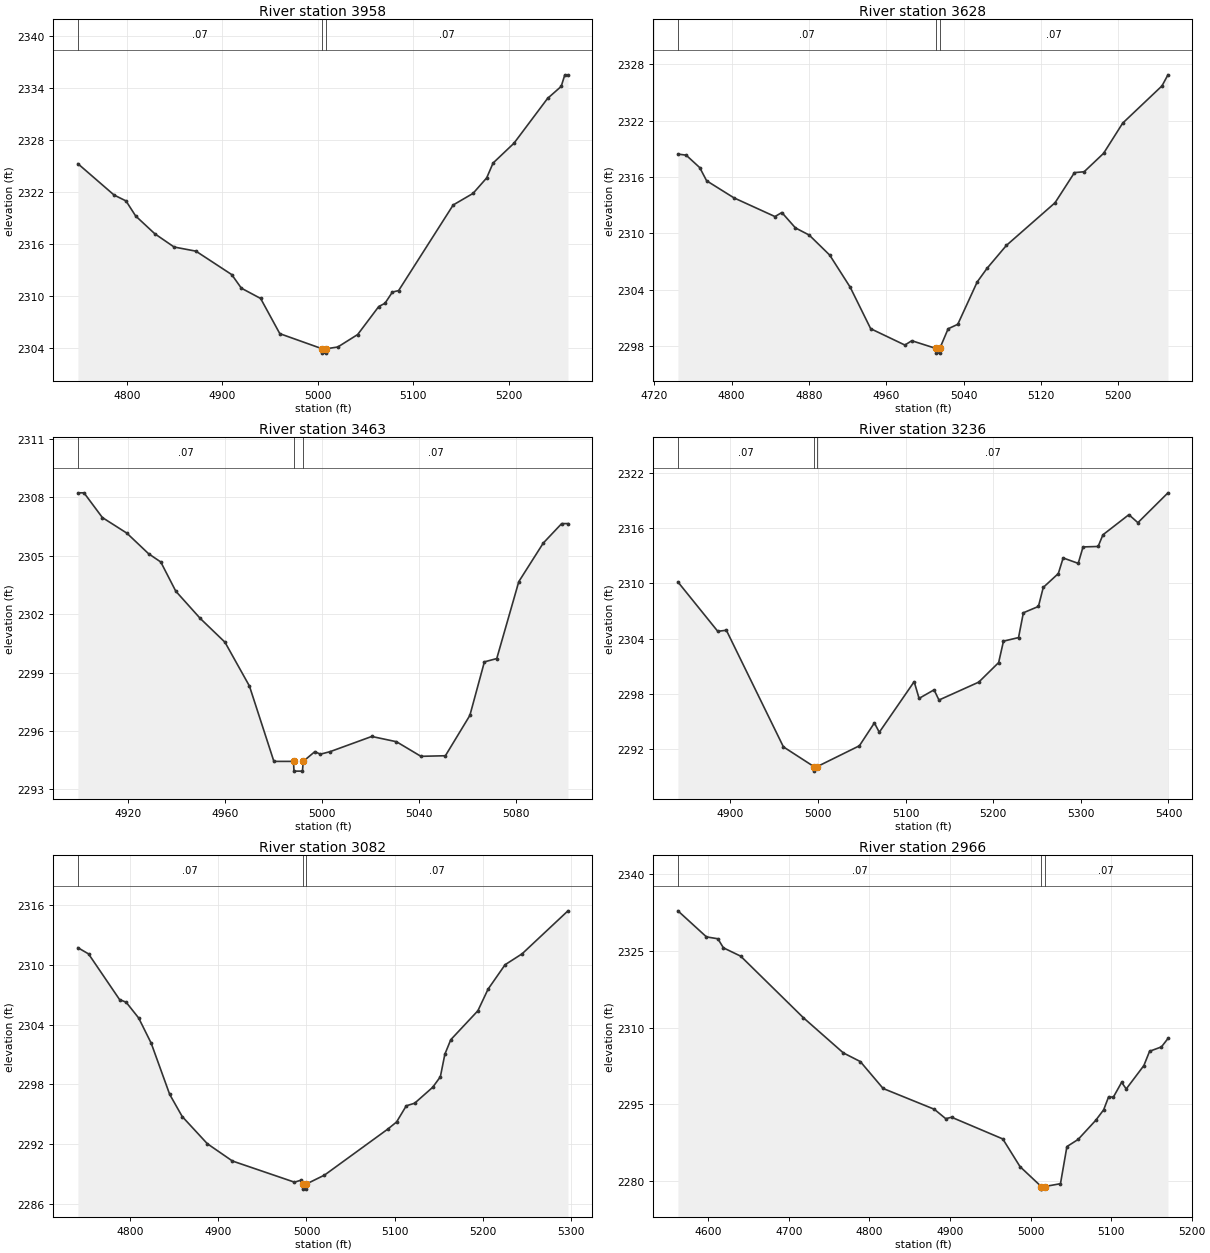
Type RM Length L Ch R = 1,3958,330,330,330
BEGIN DESCRIPTION:
Long Branch Trib3 8.0
END DESCRIPTION:
XS GIS Cut Line= 3
      1360905.00      6845637.99      1360873.92      6845388.42
      1360705.01      6845188.01
#Sta/Elev= 30
  4748.5 2325.27  4786.4 2321.65  4798.9 2320.97  4809.0 2319.23  4829.1 2317.17
  4849.3 2315.64  4872.2 2315.16  4909.7 2312.45  4919.8 2310.88  4940.0 2309.69
  4960.1 2305.62  5004.6 2303.87  5004.8 2303.37  5008.3 2303.37  5008.6 2303.87
  5020.9 2304.08  5041.7 2305.52  5063.8 2308.76  5070.3 2309.13  5078.1 2310.43
  5084.6 2310.60  5141.8 2320.50  5162.6 2321.84  5176.9 2323.63  5183.6 2325.35
  5205.5 2327.64  5240.7 2332.82  5255.0 2334.21  5258.8 2335.55  5262.1 2335.55
#Mann=3,-1,0
  4748.5    0.07       0  5004.6    0.07       0  5008.6    0.07       0
Bank Sta=5004.6,5008.6
Exp/Cntr=0.3,0.1

Type RM Length L Ch R = 1,3628,165,165,165
BEGIN DESCRIPTION:
Long Branch Trib3 4249
END DESCRIPTION:
XS GIS Cut Line= 3
      1361249.95      6845355.08      1361068.83      6845174.87
      1360818.81      6845148.60
#Sta/Elev= 30
  4744.5 2318.43  4753.0 2318.32  4767.1 2316.99  4774.2 2315.59  4802.5 2313.77
  4844.9 2311.78  4852.0 2312.21  4866.1 2310.57  4880.3 2309.81  4901.5 2307.68
  4922.7 2304.26  4943.9 2299.84  4979.3 2298.10  4986.4 2298.56  5011.4 2297.74
  5011.6 2297.24  5015.1 2297.24  5015.4 2297.74  5024.0 2299.83  5034.0 2300.31
  5054.1 2304.82  5064.2 2306.26  5084.3 2308.71  5134.6 2313.25  5154.7 2316.46
  5164.7 2316.55  5184.8 2318.51  5204.6 2321.73  5245.2 2325.69  5251.4 2326.87
#Mann=3,-1,0
  4744.5    0.07       0  5011.4    0.07       0  5015.4    0.07       0
Bank Sta=5011.4,5015.4
Exp/Cntr=0.3,0.1

Type RM Length L Ch R = 1,3463,227,227,227
BEGIN DESCRIPTION:
Long Branch Trib3 7.0
END DESCRIPTION:
XS GIS Cut Line= 3
      1361204.96      6845037.99      1361105.41      6845022.81
      1361004.95      6845038.01
#Sta/Elev= 29
  4899.3 2308.23  4901.8 2308.23  4909.4 2306.96  4919.5 2306.16  4928.5 2305.10
  4933.5 2304.68  4939.7 2303.18  4949.8 2301.78  4960.0 2300.56  4970.1 2298.31
  4980.2 2294.44  4988.3 2294.44  4988.5 2293.94  4992.0 2293.94  4992.3 2294.44
  4997.1 2294.94  4999.4 2294.81  5003.4 2294.94  5020.6 2295.72  5030.8 2295.45
  5040.9 2294.70  5051.0 2294.73  5061.1 2296.80  5067.1 2299.55  5072.2 2299.72
  5081.3 2303.67  5091.4 2305.65  5099.0 2306.65  5101.6 2306.65
#Mann=3,-1,0
  4899.3    0.07       0  4988.3    0.07       0  4992.3    0.07       0
Bank Sta=4988.3,4992.3
Exp/Cntr=0.3,0.1

Type RM Length L Ch R = 1,3236,154,154,154
BEGIN DESCRIPTION:
Long Branch Trib3 4248
END DESCRIPTION:
XS GIS Cut Line= 3
      1361244.72      6844901.94      1361105.26      6844823.91
      1360744.70      6844995.72
#Sta/Elev= 30
  4840.2 2310.17  4885.7 2304.79  4895.5 2304.91  4960.6 2292.21  4995.3 2290.07
  4995.5 2289.57  4999.3 2290.07  5047.3 2292.33  5064.4 2294.82  5070.0 2293.80
  5109.8 2299.31  5115.4 2297.49  5132.5 2298.42  5138.1 2297.31  5183.5 2299.26
  5206.2 2301.39  5211.7 2303.72  5228.9 2304.11  5234.4 2306.81  5251.6 2307.50
  5257.1 2309.57  5274.3 2311.08  5279.8 2312.78  5297.0 2312.19  5302.5 2313.98
  5319.7 2314.03  5325.2 2315.30  5354.8 2317.49  5365.1 2316.62  5399.4 2319.87
#Mann=3,-1,0
  4840.2    0.07       0  4995.3    0.07       0  4999.3    0.07       0
Bank Sta=4995.3,4999.3
Exp/Cntr=0.3,0.1

Type RM Length L Ch R = 1,3082,116,116,116
BEGIN DESCRIPTION:
Long Branch Trib3 4247
END DESCRIPTION:
XS GIS Cut Line= 3
      1361296.84      6844842.94      1361104.61      6844669.66
      1360815.42      6844733.28
#Sta/Elev= 30
  4741.2 2311.75  4753.2 2311.13  4788.4 2306.53  4795.8 2306.27  4810.0 2304.68
  4824.2 2302.14  4845.1 2297.00  4859.3 2294.77  4887.7 2292.04  4916.1 2290.30
  4986.4 2288.17  4993.9 2288.37  4995.5 2287.97  4995.8 2287.47  4999.3 2287.47
  4999.5 2287.97  5020.4 2288.88  5091.8 2293.49  5102.0 2294.22  5113.0 2295.85
  5122.5 2296.11  5142.9 2297.71  5151.6 2298.77  5156.7 2301.04  5163.4 2302.50
  5194.1 2305.41  5205.6 2307.58  5224.9 2310.04  5244.2 2311.14  5296.1 2315.46
#Mann=3,-1,0
  4741.2    0.07       0  4995.5    0.07       0  4999.5    0.07       0
Bank Sta=4995.5,4999.5
Exp/Cntr=0.3,0.1

Type RM Length L Ch R = 1,2966,200,200,200
BEGIN DESCRIPTION:
Long Branch Trib3 6.0
END DESCRIPTION:
XS GIS Cut Line= 3
      1361455.01      6844888.01      1361154.62      6844569.66
      1361004.96      6844487.98
#Sta/Elev= 30
  4562.3 2332.76  4597.7 2327.68  4611.9 2327.31  4618.8 2325.54  4640.2 2323.92
  4717.9 2311.93  4767.6 2305.05  4788.7 2303.36  4817.0 2298.11  4880.5 2294.06
  4894.7 2292.22  4902.0 2292.50  4965.5 2288.27  4986.9 2282.87  5013.3 2278.98
  5013.5 2278.48  5017.3 2278.98  5037.1 2279.54  5045.1 2286.78  5058.9 2288.16
  5080.8 2291.89  5090.7 2293.95  5096.9 2296.51  5102.6 2296.39  5113.0 2299.31
  5118.7 2298.02  5140.6 2302.58  5147.7 2305.37  5162.4 2306.22  5170.5 2307.86
#Mann=3,-1,0
  4562.3    0.07       0  5013.3    0.07       0  5017.3    0.07       0
Bank Sta=5013.3,5017.3
Exp/Cntr=0.3,0.1

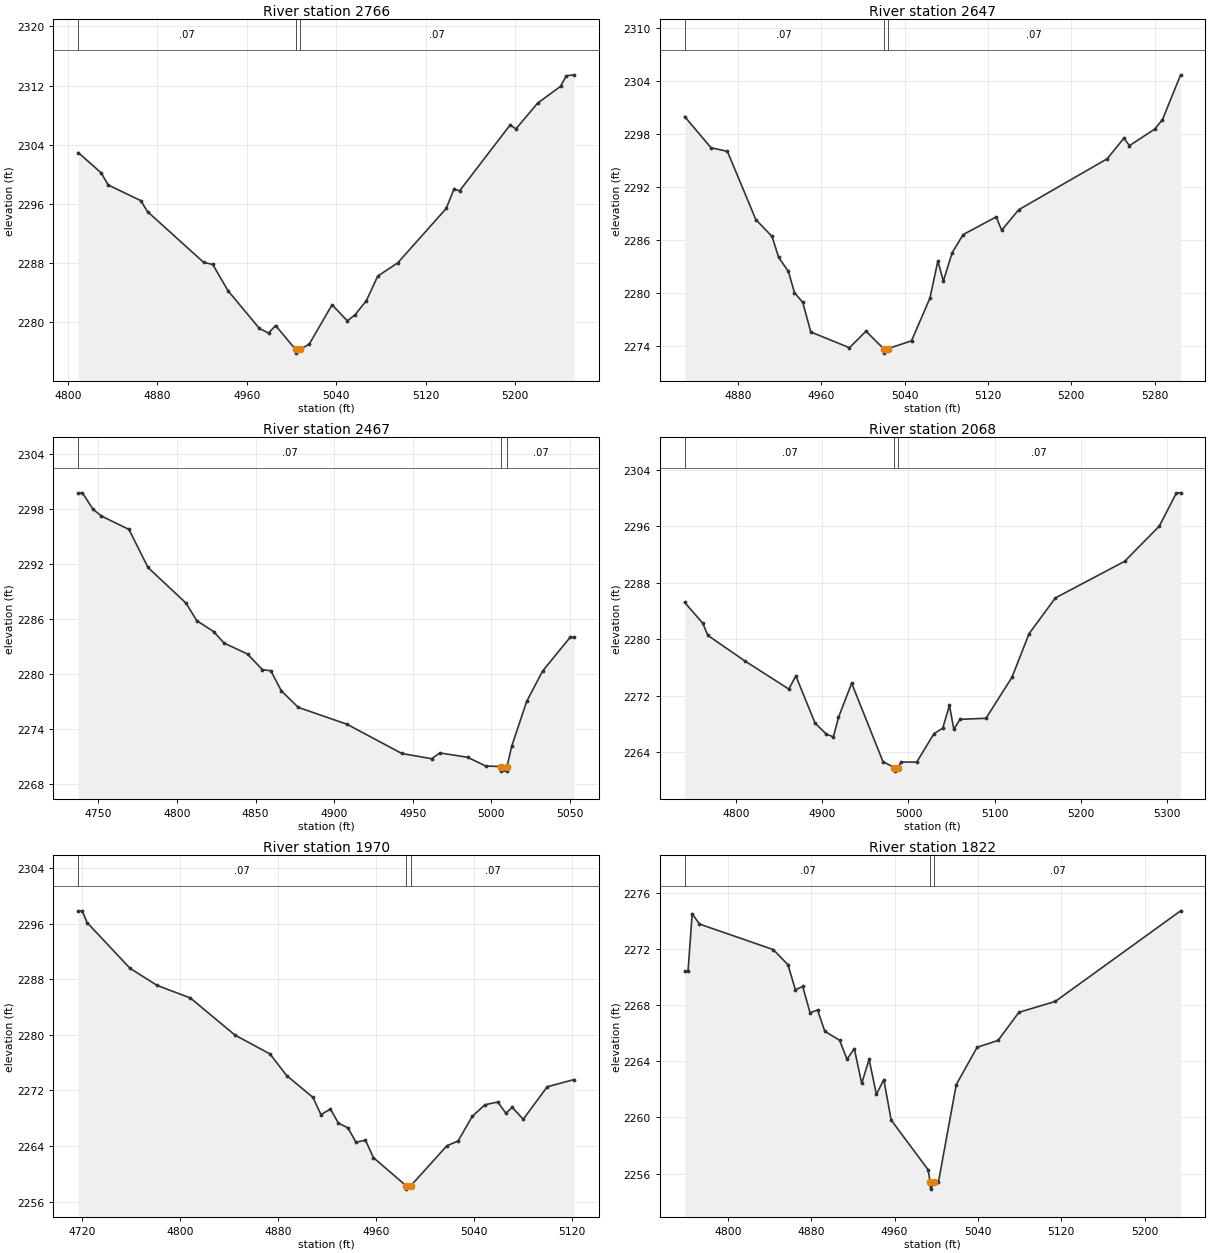
Type RM Length L Ch R = 1,2766,119,119,119
BEGIN DESCRIPTION:
Long Branch Trib3 4246
END DESCRIPTION:
XS GIS Cut Line= 3
      1361355.87      6844554.75      1361240.38      6844402.75
      1360993.01      6844351.61
#Sta/Elev= 30
  4809.1 2302.95  4829.6 2300.21  4835.9 2298.57  4865.0 2296.46  4871.2 2294.95
  4921.2 2288.12  4929.4 2287.83  4943.2 2284.25  4971.1 2279.19  4979.3 2278.56
  4985.6 2279.58  5003.5 2276.35  5003.7 2275.85  5007.5 2276.35  5015.7 2277.07
  5036.1 2282.38  5049.8 2280.21  5056.6 2281.02  5066.8 2282.94  5077.0 2286.26
  5094.9 2288.05  5138.2 2295.40  5145.1 2298.01  5150.2 2297.78  5195.4 2306.69
  5200.5 2306.14  5219.9 2309.62  5240.4 2311.89  5245.6 2313.32  5252.6 2313.45
#Mann=3,-1,0
  4809.1    0.07       0  5003.5    0.07       0  5007.5    0.07       0
Bank Sta=5003.5,5007.5
Exp/Cntr=0.3,0.1

Type RM Length L Ch R = 1,2647,180,180,180
BEGIN DESCRIPTION:
Long Branch Trib3 4245
END DESCRIPTION:
XS GIS Cut Line= 3
      1361392.31      6844455.77      1361305.50      6844308.21
      1361018.67      6844204.53
#Sta/Elev= 30
  4828.8 2299.97  4854.1 2296.45  4869.8 2296.04  4897.1 2288.33  4912.7 2286.42
  4919.0 2284.06  4928.4 2282.46  4934.2 2280.07  4942.2 2278.96  4949.9 2275.62
  4987.0 2273.84  5002.9 2275.71  5019.8 2273.73  5020.1 2273.23  5023.8 2273.73
  5046.6 2274.62  5064.3 2279.45  5071.9 2283.64  5077.2 2281.37  5085.6 2284.58
  5096.2 2286.63  5127.9 2288.63  5133.2 2287.12  5149.4 2289.43  5234.5 2295.20
  5250.5 2297.53  5255.9 2296.69  5280.1 2298.55  5287.6 2299.63  5305.0 2304.69
#Mann=3,-1,0
  4828.8    0.07       0  5019.8    0.07       0  5023.8    0.07       0
Bank Sta=5019.8,5023.8
Exp/Cntr=0.3,0.1

Type RM Length L Ch R = 1,2467,399,399,399
BEGIN DESCRIPTION:
Long Branch Trib3 5.0
END DESCRIPTION:
XS GIS Cut Line= 3
      1361454.99      6844387.97      1361357.35      6844143.97
      1361304.99      6844138.00
#Sta/Elev= 30
  4737.2 2299.75  4739.9 2299.75  4746.6 2297.96  4752.0 2297.22  4769.5 2295.76
  4781.6 2291.62  4805.8 2287.74  4812.6 2285.83  4823.3 2284.65  4830.0 2283.39
  4844.9 2282.20  4854.3 2280.51  4859.7 2280.38  4866.4 2278.20  4877.2 2276.39
  4908.1 2274.56  4943.1 2271.37  4962.0 2270.80  4967.3 2271.43  4984.9 2270.96
  4996.4 2270.01  5006.0 2269.95  5006.2 2269.45  5009.7 2269.45  5010.0 2269.95
  5013.0 2272.18  5022.5 2277.04  5032.6 2280.34  5050.2 2284.03  5052.7 2284.03
#Mann=3,-1,0
  4737.2    0.07       0  5006.0    0.07       0  5010.0    0.07       0
Bank Sta=5006,5010
Exp/Cntr=0.3,0.1

Type RM Length L Ch R = 1,2068,98,98,98
BEGIN DESCRIPTION:
Long Branch Trib3 4244
END DESCRIPTION:
XS GIS Cut Line= 3
      1361673.58      6844026.98      1361534.54      6843807.64
      1361220.42      6843841.19
#Sta/Elev= 30
  4740.3 2285.21  4761.3 2282.26  4767.2 2280.54  4810.1 2276.93  4861.2 2272.94
  4869.3 2274.81  4891.7 2268.11  4904.8 2266.56  4912.9 2266.18  4918.8 2268.93
  4934.1 2273.78  4970.5 2262.66  4983.8 2261.83  4984.1 2261.33  4987.8 2261.83
  4991.7 2262.62  5009.6 2262.60  5029.7 2266.64  5039.8 2267.41  5047.6 2270.62
  5052.7 2267.26  5059.9 2268.66  5090.0 2268.81  5120.2 2274.62  5140.0 2280.78
  5170.5 2285.84  5251.0 2291.03  5291.2 2296.02  5311.1 2300.72  5315.9 2300.72
#Mann=3,-1,0
  4740.3    0.07       0  4983.8    0.07       0  4987.8    0.07       0
Bank Sta=4983.8,4987.8
Exp/Cntr=0.3,0.1

Type RM Length L Ch R = 1,1970,148,148,148
BEGIN DESCRIPTION:
Long Branch Trib3 4.0
END DESCRIPTION:
XS GIS Cut Line= 3
      1361805.03      6843988.04      1361622.04      6843771.50
      1361505.04      6843738.01
#Sta/Elev= 30
  4716.5 2297.83  4719.8 2297.83  4723.7 2296.15  4758.8 2289.57  4780.9 2287.11
  4808.2 2285.29  4844.6 2279.96  4873.2 2277.25  4886.8 2274.14  4908.3 2271.00
  4914.8 2268.53  4922.6 2269.32  4929.1 2267.30  4936.9 2266.62  4943.4 2264.56
  4951.2 2264.84  4957.7 2262.34  4984.3 2258.31  4984.6 2257.81  4988.3 2258.31
  5017.7 2264.04  5026.9 2264.74  5038.5 2268.29  5048.9 2269.95  5059.3 2270.34
  5065.9 2268.73  5071.1 2269.57  5080.1 2267.86  5099.7 2272.53  5121.7 2273.57
#Mann=3,-1,0
  4716.5    0.07       0  4984.3    0.07       0  4988.3    0.07       0
Bank Sta=4984.3,4988.3
Exp/Cntr=0.3,0.1

Type RM Length L Ch R = 1,1822,202,202,202
BEGIN DESCRIPTION:
Long Branch Trib3 4242
END DESCRIPTION:
XS GIS Cut Line= 3
      1361864.52      6843818.61      1361694.20      6843647.67
      1361460.00      6843638.06
#Sta/Elev= 30
  4758.7 2270.39  4761.9 2270.39  4765.9 2274.49  4772.9 2273.76  4843.7 2271.94
  4857.8 2270.86  4864.9 2269.08  4871.9 2269.32  4879.0 2267.44  4886.1 2267.65
  4893.1 2266.13  4907.3 2265.49  4914.4 2264.14  4921.4 2264.90  4928.5 2262.42
  4935.6 2264.13  4942.6 2261.64  4949.7 2262.69  4956.8 2259.81  4992.1 2256.29
  4994.2 2255.40  4994.5 2254.90  4998.2 2255.40  5002.1 2255.40  5019.2 2262.34
  5039.2 2264.99  5059.3 2265.48  5079.3 2267.48  5114.1 2268.25  5234.4 2274.70
#Mann=3,-1,0
  4758.7    0.07       0  4994.2    0.07       0  4998.2    0.07       0
Bank Sta=4994.2,4998.2
Exp/Cntr=0.3,0.1

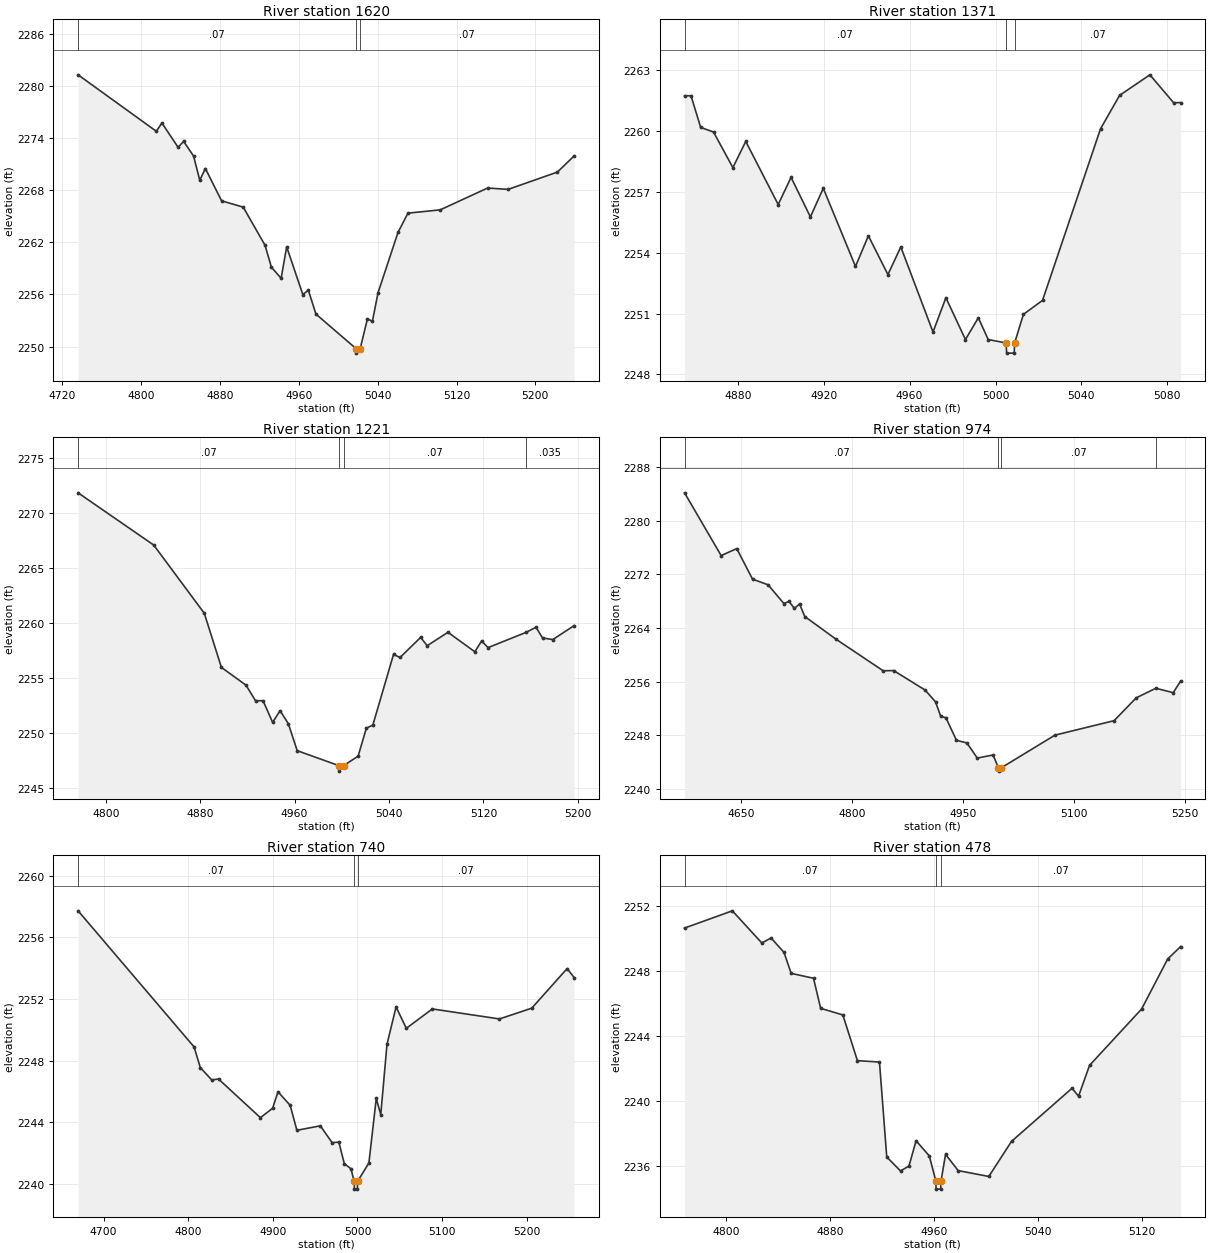
Type RM Length L Ch R = 1,1620,249,249,249
BEGIN DESCRIPTION:
Long Branch Trib3 4243
END DESCRIPTION:
XS GIS Cut Line= 3
      1361968.72      6843580.78      1361734.93      6843457.93
      1361498.22      6843493.70
#Sta/Elev= 30
  4735.9 2281.25  4815.3 2274.76  4821.0 2275.71  4837.4 2272.92  4843.0 2273.60
  4853.1 2271.92  4859.4 2269.13  4865.1 2270.48  4881.5 2266.77  4903.5 2266.04
  4925.6 2261.67  4932.1 2259.14  4942.0 2257.86  4947.6 2261.48  4964.0 2255.99
  4969.6 2256.50  4977.3 2253.75  5018.2 2249.76  5018.4 2249.26  5022.2 2249.76
  5029.6 2253.21  5034.6 2252.91  5040.4 2256.22  5060.6 2263.13  5070.7 2265.35
  5103.5 2265.73  5151.6 2268.24  5172.3 2268.08  5222.4 2270.07  5239.4 2271.93
#Mann=3,-1,0
  4735.9    0.07       0  5018.2    0.07       0  5022.2    0.07       0
Bank Sta=5018.2,5022.2
Exp/Cntr=0.3,0.1

Type RM Length L Ch R = 1,1371,150,150,150
BEGIN DESCRIPTION:
Long Branch Trib3 3.0
END DESCRIPTION:
XS GIS Cut Line= 3
      1361854.96      6843337.97      1361734.34      6843257.86
      1361663.15      6843209.25
#Sta/Elev= 30
  4855.2 2261.73  4858.2 2261.73  4862.7 2260.17  4868.7 2259.94  4877.7 2258.19
  4883.7 2259.48  4898.8 2256.37  4904.8 2257.71  4913.8 2255.76  4919.8 2257.17
  4934.8 2253.32  4940.8 2254.83  4949.9 2252.92  4955.9 2254.28  4970.9 2250.09
  4976.9 2251.78  4986.0 2249.72  4992.0 2250.79  4996.6 2249.72  5004.9 2249.55
  5005.2 2249.05  5008.7 2249.05  5008.9 2249.55  5013.0 2250.96  5021.9 2251.65
  5048.9 2260.10  5057.8 2261.75  5071.9 2262.76  5082.9 2261.39  5086.2 2261.39
#Mann=3,-1,0
  4855.2    0.07       0  5004.9    0.07       0  5008.9    0.07       0
Bank Sta=5004.9,5008.9
Exp/Cntr=0.3,0.1

Type RM Length L Ch R = 1,1221,247,247,247
BEGIN DESCRIPTION:
Long Branch Trib3 4240
END DESCRIPTION:
XS GIS Cut Line= 3
      1361994.74      6843358.55      1361857.54      6843182.25
      1361678.50      6843100.54
#Sta/Elev= 30
  4776.6 2271.79  4840.7 2267.04  4883.5 2260.84  4898.0 2255.92  4918.8 2254.31
  4926.9 2252.89  4933.3 2252.89  4941.4 2250.92  4947.7 2251.99  4954.7 2250.80
  4962.2 2248.35  4997.5 2246.99  4997.8 2246.49  5001.5 2246.99  5013.8 2247.85
  5020.8 2250.40  5026.3 2250.68  5043.8 2257.10  5049.3 2256.82  5066.8 2258.65
  5072.3 2257.89  5089.9 2259.11  5112.7 2257.34  5118.4 2258.32  5123.9 2257.72
  5156.0 2259.10  5164.5 2259.57  5170.0 2258.60  5178.7 2258.45  5196.8 2259.72
#Mann=4,-1,0
  4776.6    0.07       0  4997.5    0.07       0  5001.5    0.07       0
  5156.0   0.035       0
Bank Sta=4997.5,5001.5
Exp/Cntr=0.3,0.1

Type RM Length L Ch R = 1,974,234,234,234
BEGIN DESCRIPTION:
Long Branch Trib3 2.0
END DESCRIPTION:
XS GIS Cut Line= 3
      1362304.97      6843287.97      1361999.53      6842990.45
      1361755.04      6842988.00
#Sta/Elev= 30
  4573.6 2284.18  4623.1 2274.81  4644.2 2275.86  4665.5 2271.30  4686.6 2270.45
  4707.9 2267.66  4714.9 2267.97  4722.1 2266.92  4729.1 2267.59  4736.2 2265.72
  4778.7 2262.31  4842.2 2257.62  4856.4 2257.65  4898.8 2254.75  4913.0 2252.99
  4920.1 2250.80  4927.1 2250.61  4941.3 2247.24  4955.4 2246.85  4969.5 2244.59
  4990.9 2245.05  4998.0 2243.14  4998.2 2242.64  5002.0 2243.14  5074.5 2248.01
  5154.5 2250.17  5184.5 2253.58  5211.0 2255.01  5234.5 2254.35  5244.5 2256.08
#Mann=4,-1,0
  4573.6    0.07       0  4998.0    0.07       0  5002.0    0.07       0
  5211.0   0.035       0
Bank Sta=4998,5002
Exp/Cntr=0.3,0.1

Type RM Length L Ch R = 1,740,262,262,262
BEGIN DESCRIPTION:
Long Branch Trib3 4239
END DESCRIPTION:
XS GIS Cut Line= 3
      1362236.05      6843019.99      1362027.66      6842763.98
      1361788.16      6842854.41
#Sta/Elev= 30
  4669.9 2257.72  4807.0 2248.88  4814.3 2247.54  4827.8 2246.74  4835.8 2246.80
  4885.3 2244.29  4899.7 2244.90  4906.1 2245.97  4920.5 2245.09  4928.4 2243.47
  4956.1 2243.76  4970.0 2242.67  4978.0 2242.70  4984.4 2241.31  4992.3 2240.97
  4996.1 2240.15  4996.4 2239.65  4999.9 2239.65  5000.1 2240.15  5013.5 2241.35
  5022.2 2245.54  5027.5 2244.49  5034.9 2249.06  5045.6 2251.48  5057.7 2250.09
  5088.4 2251.35  5167.8 2250.70  5205.9 2251.40  5247.7 2253.97  5256.0 2253.39
#Mann=3,-1,0
  4669.9    0.07       0  4996.1    0.07       0  5000.1    0.07       0
Bank Sta=4996.1,5000.1
Exp/Cntr=0.3,0.1

Type RM Length L Ch R = 1,478,0,0,0
BEGIN DESCRIPTION:
Long Branch Trib3 1.0
END DESCRIPTION:
XS GIS Cut Line= 3
      1362305.01      6842838.03      1362204.86      6842628.87
      1362055.04      6842638.00
#Sta/Elev= 30
  4768.1 2250.62  4804.9 2251.68  4827.6 2249.70  4834.7 2250.01  4844.7 2249.12
  4850.2 2247.83  4867.4 2247.53  4872.9 2245.68  4890.0 2245.27  4901.2 2242.46
  4918.2 2242.37  4923.8 2236.53  4934.4 2235.67  4940.9 2235.97  4946.4 2237.53
  4956.6 2236.59  4961.6 2235.05  4961.8 2234.55  4965.3 2234.55  4965.6 2235.05
  4969.1 2236.69  4978.8 2235.69  5002.4 2235.33  5019.9 2237.49  5066.5 2240.76
  5071.5 2240.27  5080.0 2242.17  5120.1 2245.64  5140.1 2248.71  5150.1 2249.48
#Mann=3,-1,0
  4768.1    0.07       0  4961.6    0.07       0  4965.6    0.07       0
Bank Sta=4961.6,4965.6
Exp/Cntr=0.3,0.1

Chan Stop Cuts=-1