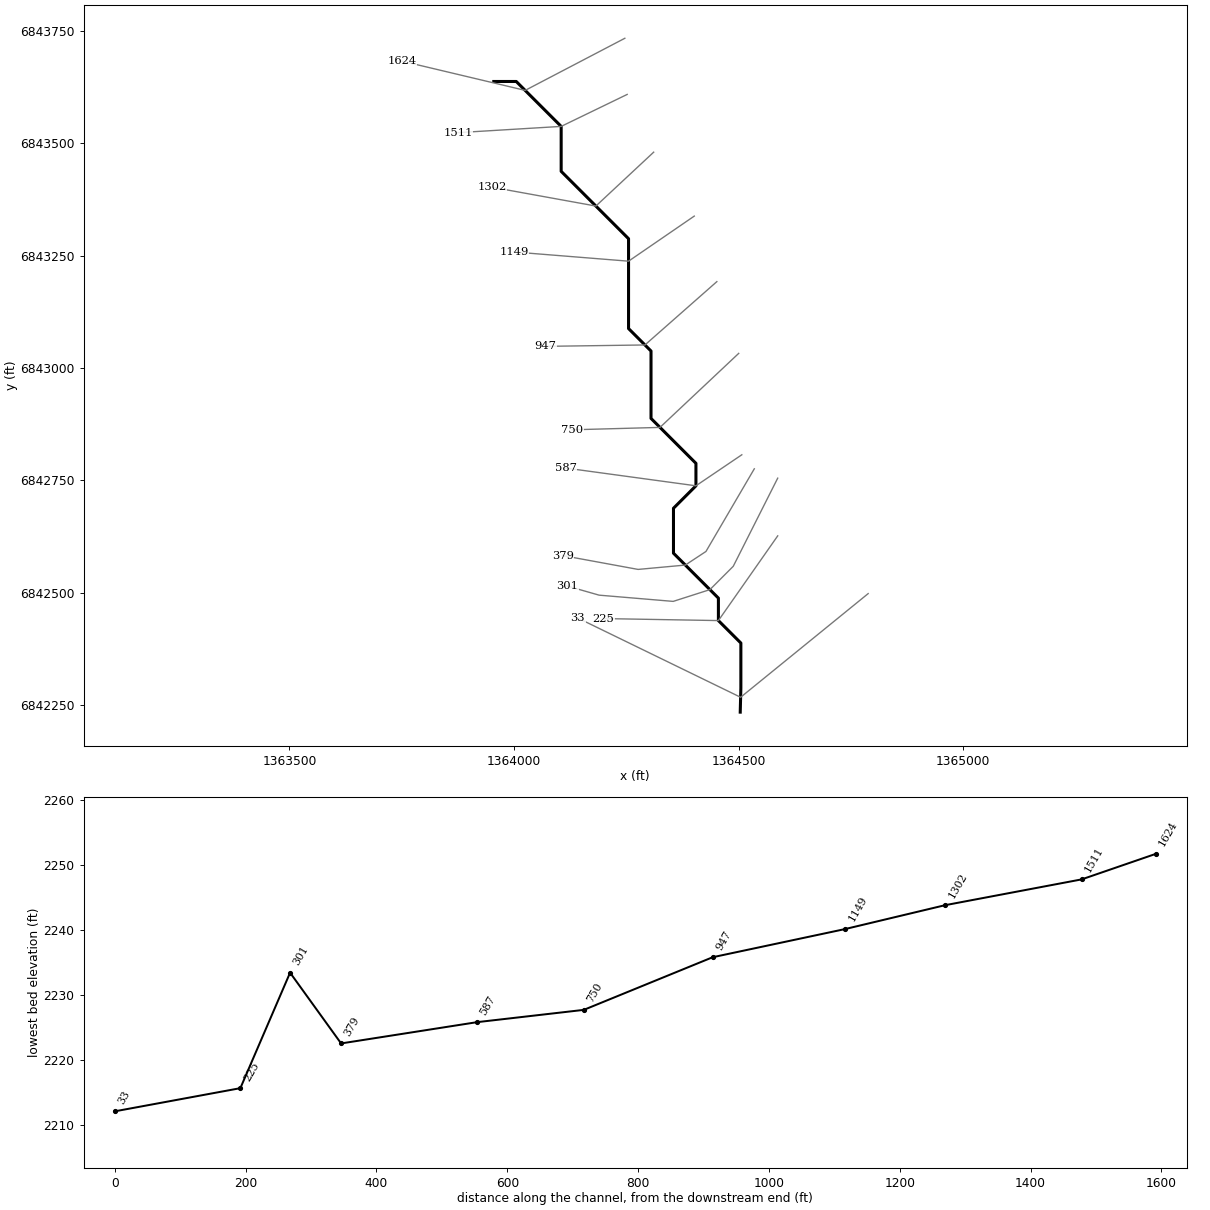
--- Long Branch Trib 3_4.prj (project) ---

Proj Title=Long Branch Trib 3_4 Base Level Engineering
Current Plan=p01
Default Exp/Contr=0.3,0.1
English Units
Geom File=g01
Flow File=f01
Plan File=p01
BEGIN DESCRIPTION:
Long Branch Trib 3_4
END DESCRIPTION:

--- Long Branch Trib 3_4.p01 (plan) ---

Plan Title=Multiple Run
Short Identifier=Multiple
Geom File=g01
Flow File=f01
Subcritical Flow
K Sum by GR= 0
Std Step Tol= 0.01
Critical Tol= 0.01
Num of Std Step Trials= 20
Max Error Tol= 0.3
Flow Tol Ratio= 0.001
Split Flow NTrial= 30
Split Flow Tol= 0.02
Split Flow Ratio= 0.02
Log Output Level= 0
Friction Slope Method= 1
Unsteady Friction Slope Method= 2
Unsteady Bridges Friction Slope Method= 1
Parabolic Critical Depth
Global Vel Dist=  1 , 1 , 1
Global Log Level= 0
CheckData=True
Encroach Param= -1, 0, 0, 0
BEGIN DESCRIPTION:
Multiple Run
END DESCRIPTION:

--- Long Branch Trib 3_4.f01 (steady flow) ---

Flow Title=Multiple
Number of Profiles=7
Profile Names=10-year,25-year,50-year,1pct_min,100-year,1pct_plu,500-year
River Rch & RM= Long Branch Trib,Reach-1,1624
      49      63      73      43      86     171     118
Boundary for River Rch & Prof#=Long Branch Trib,Reach-1,1
Up Type=0
Dn Type=3
Dn Slope=0.005
Boundary for River Rch & Prof#=Long Branch Trib,Reach-1,2
Up Type=0
Dn Type=3
Dn Slope=0.005
Boundary for River Rch & Prof#=Long Branch Trib,Reach-1,3
Up Type=0
Dn Type=3
Dn Slope=0.005
Boundary for River Rch & Prof#=Long Branch Trib,Reach-1,4
Up Type=0
Dn Type=3
Dn Slope=0.005
Boundary for River Rch & Prof#=Long Branch Trib,Reach-1,5
Up Type=0
Dn Type=3
Dn Slope=0.005
Boundary for River Rch & Prof#=Long Branch Trib,Reach-1,6
Up Type=0
Dn Type=3
Dn Slope=0.005
Boundary for River Rch & Prof#=Long Branch Trib,Reach-1,7
Up Type=0
Dn Type=3
Dn Slope=0.005

--- Long Branch Trib 3_4.g01 (geometry) ---

Geom Title=Existing Conditions

River Reach=Long Branch Trib,Reach-1
Reach XY= 30
      1363955.00      6843638.00      1364005.00      6843638.00
      1364055.00      6843588.00      1364105.00      6843538.00
      1364105.00      6843488.00      1364105.00      6843438.00
      1364155.00      6843388.00      1364205.00      6843338.00
      1364255.00      6843288.00      1364255.00      6843238.00
      1364255.00      6843188.00      1364255.00      6843138.00
      1364255.00      6843088.00      1364305.00      6843038.00
      1364305.00      6842988.00      1364305.00      6842938.00
      1364305.00      6842888.00      1364355.00      6842838.00
      1364405.00      6842788.00      1364405.00      6842738.00
      1364355.00      6842688.00      1364355.00      6842638.00
      1364355.00      6842588.00      1364405.00      6842538.00
      1364455.00      6842488.00      1364455.00      6842438.00
      1364505.00      6842388.00      1364505.00      6842338.00
      1364505.00      6842288.00      1364503.60      6842234.17

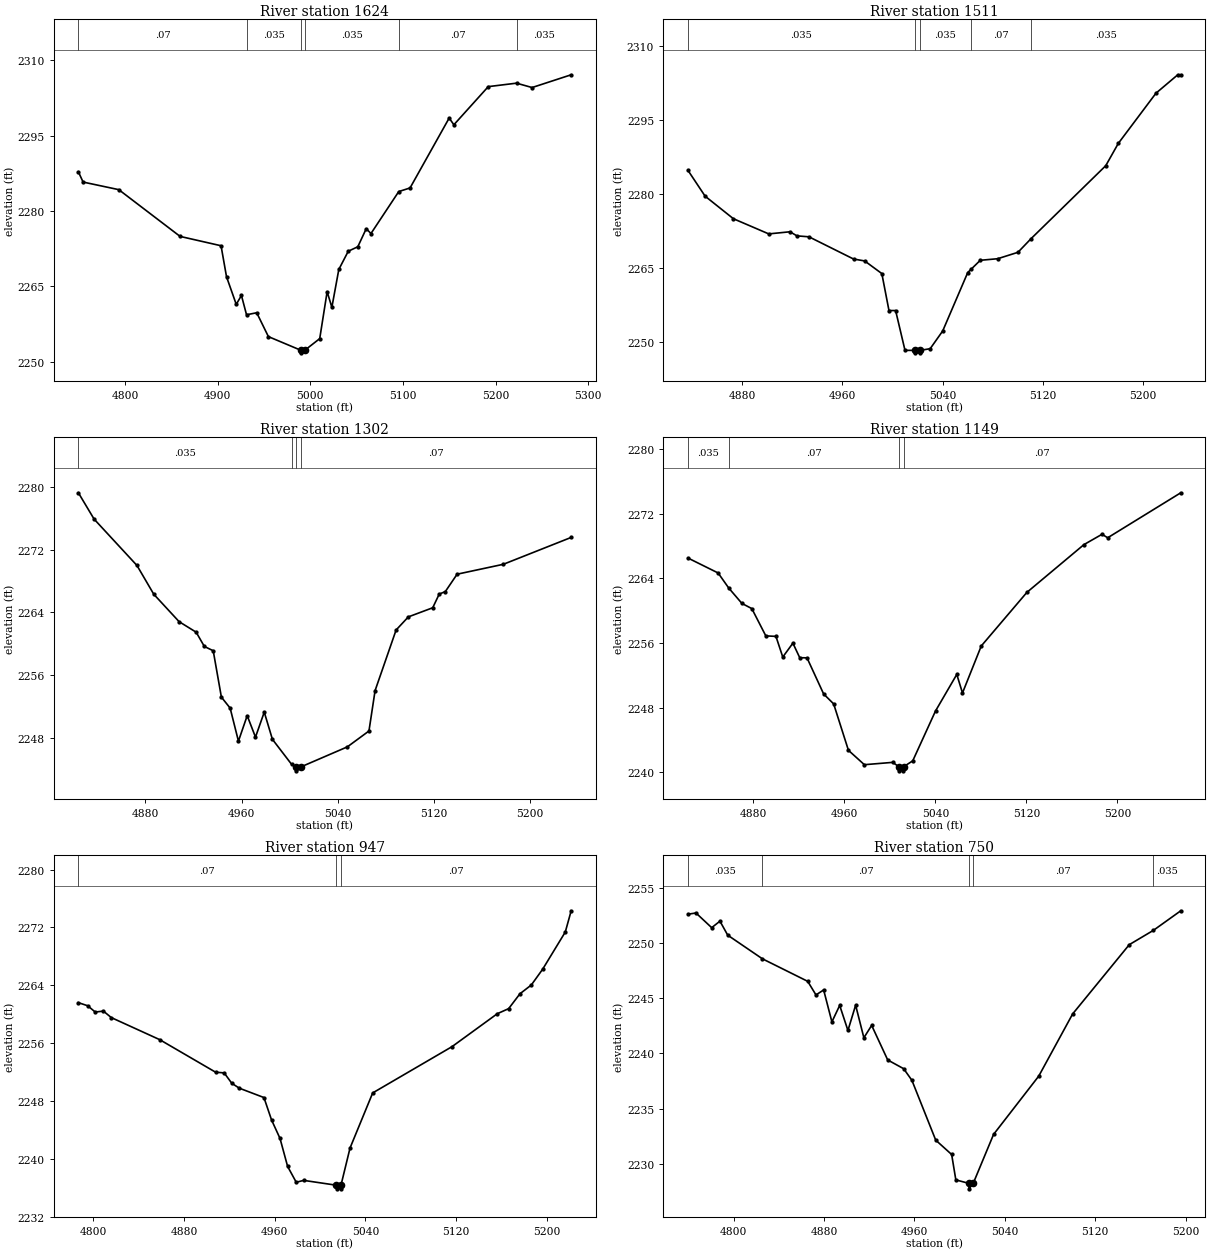
Type RM Length L Ch R = 1,1624,113,113,113
BEGIN DESCRIPTION:
Long Branch Trib 3_4 4259
END DESCRIPTION:
XS GIS Cut Line= 3
      1364246.74      6843734.17      1364024.83      6843618.17
      1363750.95      6843683.23
#Sta/Elev= 30
  4749.6 2287.79  4754.7 2285.75  4793.2 2284.24  4859.4 2274.93  4903.6 2273.07
  4909.5 2266.90  4920.0 2261.40  4925.6 2263.18  4931.1 2259.33  4942.1 2259.73
  4954.7 2254.98  4989.9 2252.25  4990.1 2251.75  4993.9 2252.25  5010.1 2254.58
  5018.1 2263.93  5023.2 2260.81  5030.7 2268.35  5040.9 2271.98  5051.2 2272.87
  5060.3 2276.47  5065.4 2275.50  5095.4 2283.86  5107.6 2284.58  5149.8 2298.49
  5154.9 2297.16  5192.0 2304.75  5222.5 2305.44  5239.3 2304.57  5281.5 2307.11
#Mann=6,-1,0
  4749.6    0.07       0  4931.1   0.035       0  4989.9   0.035       0
  4993.9   0.035       0  5095.4    0.07       0  5222.5   0.035       0
Bank Sta=4989.9,4993.9
Exp/Cntr=0.3,0.1

Type RM Length L Ch R = 1,1511,209,209,209
BEGIN DESCRIPTION:
Long Branch Trib 3_4 4258
END DESCRIPTION:
XS GIS Cut Line= 3
      1364251.97      6843609.19      1364105.00      6843538.00
      1363875.22      6843524.10
#Sta/Elev= 30
  4836.7 2284.80  4850.4 2279.57  4873.0 2275.00  4901.2 2271.93  4918.2 2272.36
  4923.7 2271.53  4933.3 2271.34  4968.9 2266.84  4977.8 2266.45  4991.5 2263.89
  4997.2 2256.40  5002.5 2256.40  5010.0 2248.33  5018.0 2248.33  5018.3 2247.83
  5021.8 2247.83  5022.0 2248.33  5030.1 2248.67  5040.1 2252.26  5060.1 2264.10
  5062.6 2264.72  5070.1 2266.58  5084.0 2266.90  5100.2 2268.20  5110.4 2270.90
  5170.3 2285.75  5180.3 2290.26  5210.4 2300.44  5227.8 2304.17  5230.2 2304.17
#Mann=5,-1,0
  4836.7   0.035       0  5018.0   0.035       0  5022.0   0.035       0
  5062.6    0.07       0  5110.4   0.035       0
Bank Sta=5018,5022
Exp/Cntr=0.3,0.1

Type RM Length L Ch R = 1,1302,153,153,153
BEGIN DESCRIPTION:
Long Branch Trib 3_4 4257
END DESCRIPTION:
XS GIS Cut Line= 3
      1364310.94      6843480.67      1364182.29      6843360.71
      1363951.56      6843402.58
#Sta/Elev= 30
  4824.1 2279.23  4837.2 2275.88  4872.9 2269.98  4886.9 2266.32  4908.0 2262.83
  4922.2 2261.49  4929.0 2259.68  4936.4 2259.13  4943.2 2253.23  4950.5 2251.83
  4957.4 2247.63  4964.7 2250.87  4971.6 2248.14  4978.9 2251.32  4985.7 2247.86
  5001.7 2244.67  5005.4 2244.35  5005.7 2243.85  5009.4 2244.35  5048.1 2246.90
  5066.1 2248.92  5071.2 2254.06  5088.7 2261.77  5098.9 2263.44  5119.2 2264.60
  5124.6 2266.34  5129.7 2266.66  5139.5 2268.87  5178.0 2270.13  5234.5 2273.55
#Mann=4,-1,0
  4824.1   0.035       0  5001.7    0.07       0  5005.4   0.035       0
  5009.4    0.07       0
Bank Sta=5005.4,5009.4
Exp/Cntr=0.3,0.1

Type RM Length L Ch R = 1,1149,202,202,202
BEGIN DESCRIPTION:
Long Branch Trib 3_4 4256
END DESCRIPTION:
XS GIS Cut Line= 3
      1364401.28      6843338.36      1364255.00      6843238.00
      1364000.22      6843258.47
#Sta/Elev= 30
  4822.6 2266.52  4849.1 2264.67  4858.4 2262.81  4870.0 2260.90  4878.7 2260.26
  4891.0 2256.88  4899.9 2256.82  4905.9 2254.26  4914.8 2255.98  4920.8 2254.18
  4927.2 2254.16  4941.8 2249.69  4950.6 2248.46  4963.6 2242.71  4977.6 2240.93
  5002.5 2241.22  5008.0 2240.67  5008.3 2240.17  5011.8 2240.17  5012.0 2240.67
  5020.1 2241.41  5040.1 2247.58  5058.8 2252.11  5063.8 2249.81  5080.3 2255.63
  5120.4 2262.27  5170.5 2268.18  5186.4 2269.46  5191.4 2269.03  5255.6 2274.60
#Mann=4,-1,0
  4822.6   0.035       0  4858.4    0.07       0  5008.0    0.07       0
  5012.0    0.07       0
Bank Sta=5008,5012
Exp/Cntr=0.3,0.1

Type RM Length L Ch R = 1,947,197,197,197
BEGIN DESCRIPTION:
Long Branch Trib 3_4 4255
END DESCRIPTION:
XS GIS Cut Line= 3
      1364451.56      6843192.48      1364291.49      6843051.51
      1364069.82      6843048.41
#Sta/Elev= 30
  4786.7 2261.60  4794.9 2261.17  4801.6 2260.30  4808.8 2260.43  4815.8 2259.53
  4858.5 2256.48  4907.8 2251.98  4915.4 2251.88  4922.1 2250.45  4928.7 2249.77
  4950.5 2248.47  4957.2 2245.38  4964.7 2242.81  4971.4 2238.94  4979.0 2236.75
  4985.6 2237.01  5014.5 2236.34  5014.7 2235.84  5018.2 2235.84  5018.5 2236.34
  5026.5 2241.49  5046.5 2249.11  5116.5 2255.51  5156.5 2260.07  5166.5 2260.77
  5176.5 2262.83  5186.5 2264.04  5196.5 2266.22  5216.5 2271.37  5221.7 2274.31
#Mann=3,-1,0
  4786.7    0.07       0  5014.5    0.07       0  5018.5    0.07       0
Bank Sta=5014.5,5018.5
Exp/Cntr=0.3,0.1

Type RM Length L Ch R = 1,750,163,163,163
BEGIN DESCRIPTION:
Long Branch Trib 3_4 4254
END DESCRIPTION:
XS GIS Cut Line= 3
      1364500.19      6843032.77      1364325.00      6842868.00
      1364129.37      6842862.66
#Sta/Elev= 30
  4759.5 2252.60  4766.6 2252.71  4780.5 2251.38  4787.8 2251.97  4794.7 2250.70
  4825.4 2248.56  4865.5 2246.52  4872.8 2245.29  4879.6 2245.74  4886.9 2242.85
  4893.8 2244.34  4901.1 2242.07  4907.9 2244.36  4915.2 2241.41  4922.1 2242.53
  4936.3 2239.40  4950.4 2238.61  4957.7 2237.56  4978.8 2232.14  4992.9 2230.84
  4996.6 2228.54  5008.0 2228.23  5008.3 2227.73  5012.0 2228.23  5030.0 2232.66
  5070.0 2237.94  5100.0 2243.57  5150.1 2249.84  5171.5 2251.14  5195.7 2252.91
#Mann=5,-1,0
  4759.5   0.035       0  4825.4    0.07       0  5008.0    0.07       0
  5012.0    0.07       0  5171.5   0.035       0
Bank Sta=5008,5012
Exp/Cntr=0.3,0.1

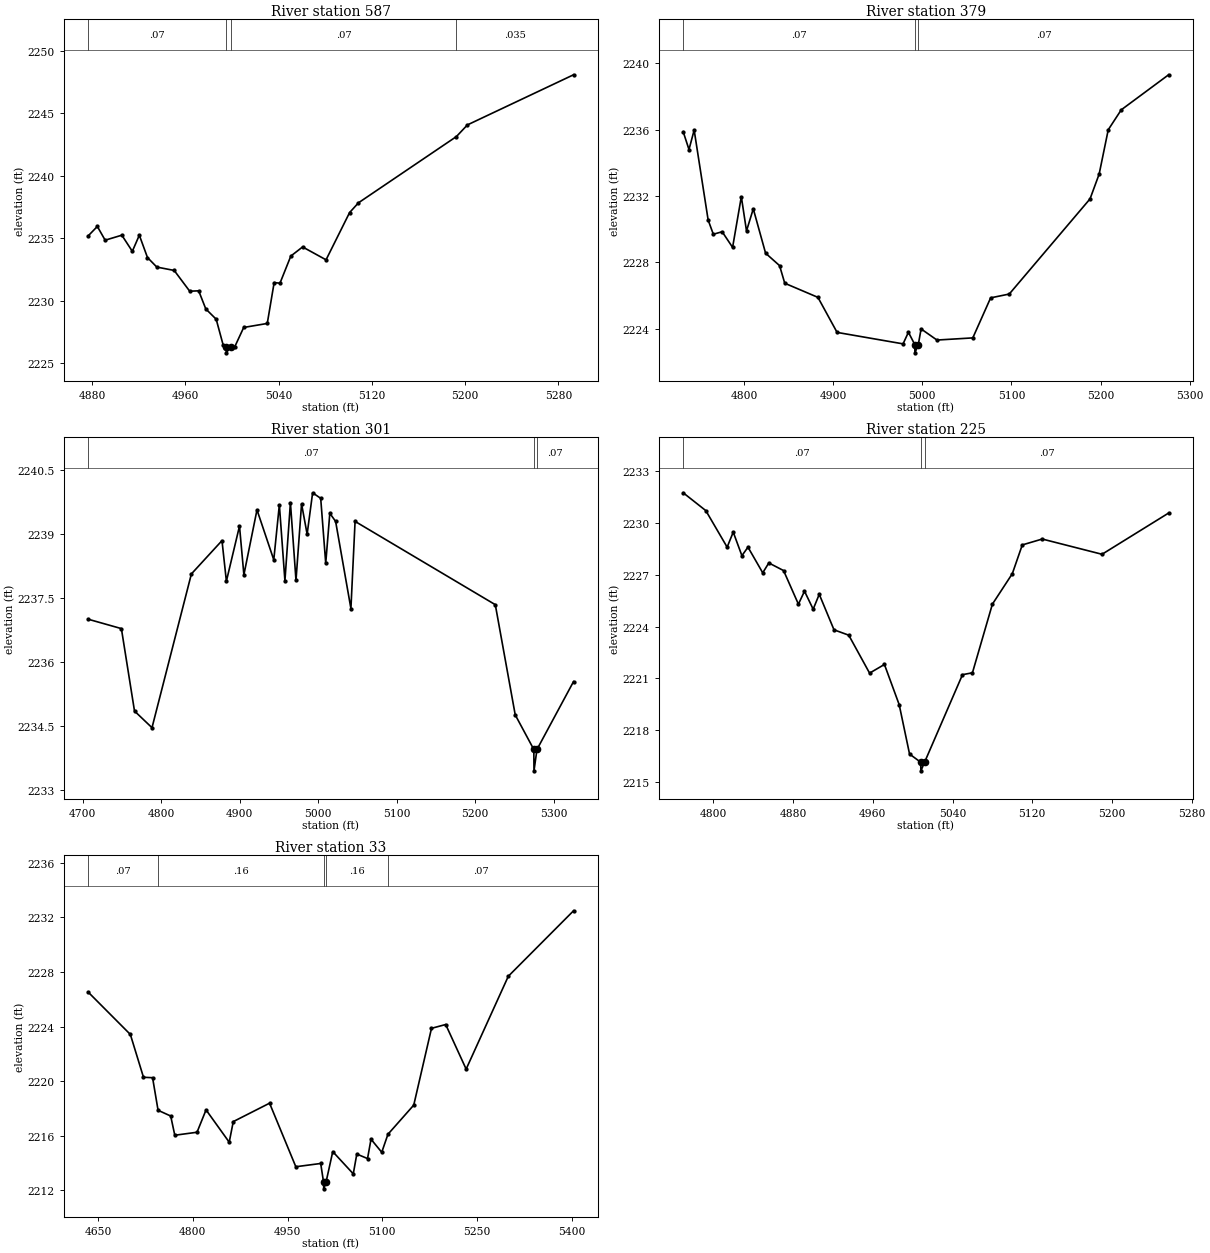
Type RM Length L Ch R = 1,587,208,208,208
BEGIN DESCRIPTION:
Long Branch Trib 3_4 4253
END DESCRIPTION:
XS GIS Cut Line= 3
      1364507.13      6842807.08      1364405.00      6842738.00
      1364114.79      6842777.57
#Sta/Elev= 30
  4876.7 2235.19  4884.6 2235.95  4891.3 2234.85  4905.6 2235.25  4914.6 2233.96
  4920.6 2235.25  4927.6 2233.46  4935.6 2232.70  4950.5 2232.43  4963.8 2230.77
  4971.5 2230.80  4977.6 2229.35  4986.5 2228.53  4992.5 2226.46  4995.0 2226.34
  4995.2 2225.84  4999.0 2226.34  5002.5 2226.34  5010.1 2227.87  5030.3 2228.19
  5036.2 2231.46  5041.2 2231.41  5050.5 2233.58  5060.6 2234.31  5080.7 2233.28
  5100.9 2237.06  5108.5 2237.84  5192.5 2243.14  5201.9 2244.07  5292.9 2248.08
#Mann=4,-1,0
  4876.7    0.07       0  4995.0    0.07       0  4999.0    0.07       0
  5192.5   0.035       0
Bank Sta=4995,4999
Exp/Cntr=0.3,0.1

Type RM Length L Ch R = 1,379,78,78,78
BEGIN DESCRIPTION:
Long Branch Trib 3_4 4252
END DESCRIPTION:
XS GIS Cut Line= 5
      1364534.91      6842775.82      1364427.28      6842591.81
      1364381.42      6842561.58      1364276.24      6842551.88
      1364108.38      6842582.71
#Sta/Elev= 30
  4731.9 2235.87  4738.4 2234.80  4744.2 2235.97  4759.9 2230.55  4765.7 2229.70
  4775.6 2229.85  4787.3 2228.91  4797.1 2231.96  4802.9 2229.90  4810.5 2231.23
  4824.3 2228.56  4840.0 2227.81  4845.8 2226.75  4883.0 2225.90  4904.5 2223.79
  4978.5 2223.10  4984.5 2223.80  4991.6 2223.06  4991.8 2222.56  4995.6 2223.06
  4998.7 2224.00  5016.5 2223.33  5056.7 2223.46  5076.7 2225.87  5097.6 2226.10
  5188.2 2231.83  5198.4 2233.32  5208.6 2235.99  5223.2 2237.19  5276.3 2239.30
#Mann=3,-1,0
  4731.9    0.07       0  4991.6    0.07       0  4995.6    0.07       0
Bank Sta=4991.6,4995.6
Exp/Cntr=0.3,0.1

Type RM Length L Ch R = 1,301,76,76,76
BEGIN DESCRIPTION:
Long Branch Trib 3_4 4251
END DESCRIPTION:
XS GIS Cut Line= 6
      1364587.02      6842755.03      1364488.05      6842558.82
      1364436.11      6842506.89      1364354.37      6842480.70
      1364189.44      6842494.59      1364118.24      6842514.93
#Sta/Elev= 30
  4706.8 2237.01  4749.2 2236.79  4765.9 2234.86  4788.2 2234.47  4838.4 2238.07
  4877.4 2238.85  4883.0 2237.90  4899.7 2239.19  4905.3 2238.05  4922.0 2239.57
  4943.4 2238.40  4950.5 2239.69  4957.6 2237.91  4964.6 2239.74  4971.7 2237.92
  4978.8 2239.71  4985.9 2239.00  4992.9 2239.97  5003.2 2239.84  5009.6 2238.32
  5014.8 2239.49  5022.2 2239.30  5041.7 2237.26  5047.0 2239.30  5225.7 2237.35
  5251.1 2234.77  5274.8 2233.96  5275.0 2233.46  5278.8 2233.96  5325.4 2235.55
#Mann=3,-1,0
  4706.8    0.07       0  5274.8    0.07       0  5278.8    0.07       0
Bank Sta=5274.8,5278.8
Exp/Cntr=0.3,0.1

Type RM Length L Ch R = 1,225,192,192,192
BEGIN DESCRIPTION:
Long Branch Trib 3_4 4250
END DESCRIPTION:
XS GIS Cut Line= 3
      1364587.03      6842626.57      1364455.00      6842438.00
      1364198.24      6842442.47
#Sta/Elev= 30
  4769.8 2231.72  4792.5 2230.69  4813.9 2228.58  4820.0 2229.45  4828.7 2228.09
  4834.8 2228.58  4849.6 2227.10  4855.7 2227.67  4870.5 2227.23  4885.4 2225.29
  4891.5 2226.04  4900.2 2225.00  4906.3 2225.86  4921.1 2223.81  4935.9 2223.50
  4956.8 2221.31  4971.7 2221.81  4986.5 2219.49  4996.9 2216.64  5008.0 2216.17
  5008.3 2215.67  5012.0 2216.17  5050.0 2221.22  5060.0 2221.33  5080.0 2225.29
  5100.0 2227.05  5110.0 2228.71  5130.0 2229.05  5190.0 2228.17  5256.8 2230.55
#Mann=3,-1,0
  4769.8    0.07       0  5008.0    0.07       0  5012.0    0.07       0
Bank Sta=5008,5012
Exp/Cntr=0.3,0.1

Type RM Length L Ch R = 1,33,0,0,0
BEGIN DESCRIPTION:
Long Branch Trib 3_4 4249
END DESCRIPTION:
XS GIS Cut Line= 3
      1364788.40      6842498.06      1364504.46      6842267.27
      1364142.10      6842443.62
#Sta/Elev= 30
  4634.1 2226.53  4701.0 2223.42  4721.8 2220.28  4736.2 2220.25  4744.9 2217.86
  4764.9 2217.44  4771.4 2216.03  4806.6 2216.25  4820.9 2217.89  4857.6 2215.52
  4864.0 2217.03  4921.5 2218.38  4963.1 2213.72  5002.5 2213.96  5007.0 2212.60
  5007.3 2212.10  5011.0 2212.60  5021.6 2214.83  5054.1 2213.20  5059.7 2214.65
  5076.7 2214.32  5082.2 2215.74  5099.2 2214.78  5109.0 2216.10  5149.9 2218.24
  5178.0 2223.87  5200.5 2224.15  5232.9 2220.88  5299.7 2227.69  5403.0 2232.49
#Mann=5,-1,0
  4634.1    0.07       0  4744.9    0.16       0  5007.0    0.07       0
  5011.0    0.16       0  5109.0    0.07       0
Bank Sta=5007,5011
Exp/Cntr=0.3,0.1

Chan Stop Cuts=-1