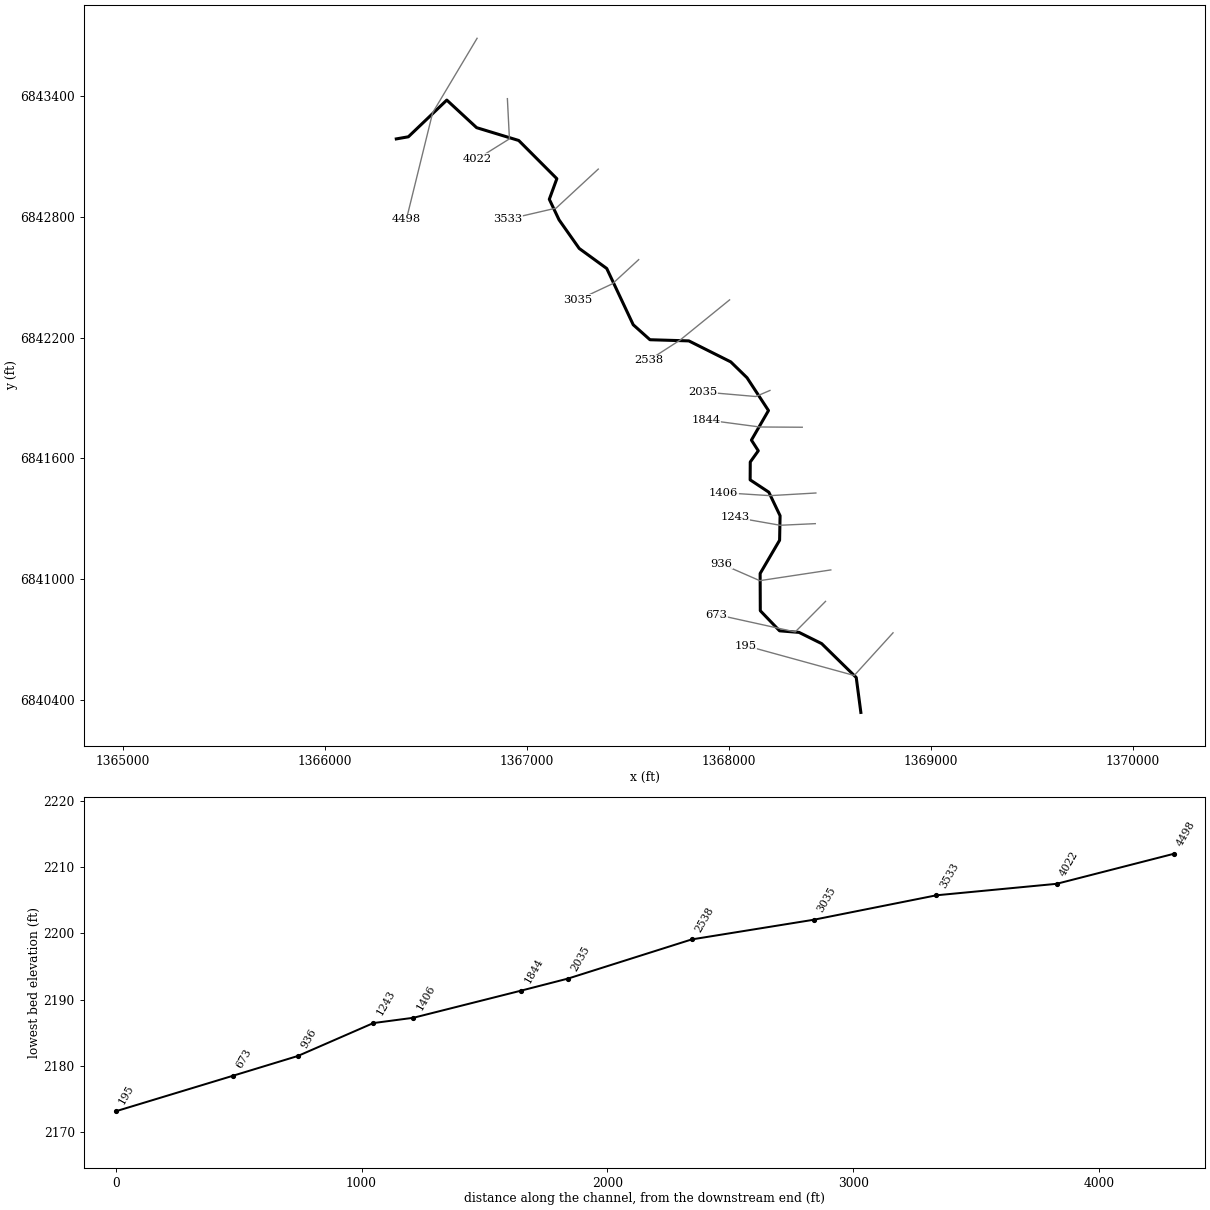
--- Long Branch Trib4.prj (project) ---

Proj Title=Long Branch Trib4 Base Level Engineering
Current Plan=p01
Default Exp/Contr=0.3,0.1
English Units
Geom File=g01
Flow File=f01
Plan File=p01
Y Axis Title=Elevation
X Axis Title(PF)=Main Channel Distance
X Axis Title(XS)=Station
BEGIN DESCRIPTION:
Long Branch Trib4
END DESCRIPTION:
DSS Export Rating Curves= 0
DSS Export Rating Curve Sorted= 0
DSS Export Volume Flow Curves= 0
DXF OffsetX= 0
DXF OffsetY= 0
DXF ScaleX= 1
DXF ScaleY= 10

--- Long Branch Trib4.p01 (plan) ---

Plan Title=Multiple Run
Short Identifier=Multiple
Geom File=g01
Flow File=f01
Subcritical Flow
K Sum by GR= 0
Std Step Tol= 0.01
Critical Tol= 0.01
Num of Std Step Trials= 20
Max Error Tol= 0.3
Flow Tol Ratio= 0.001
Split Flow NTrial= 30
Split Flow Tol= 0.02
Split Flow Ratio= 0.02
Log Output Level= 0
Friction Slope Method= 1
Unsteady Friction Slope Method= 2
Unsteady Bridges Friction Slope Method= 1
Parabolic Critical Depth
Global Vel Dist=  1 , 1 , 1
Global Log Level= 0
CheckData=True
Encroach Param= -1, 0, 0, 0
BEGIN DESCRIPTION:
Multiple Run
END DESCRIPTION:

--- Long Branch Trib4.f01 (steady flow) ---

Flow Title=Multiple
Number of Profiles=7
Profile Names=10-year,25-year,50-year,1pct_min,100-year,1pct_plu,500-year
River Rch & RM= Long Branch Trib,Reach-1,4498
     154     213     262     161     320     639     485
Boundary for River Rch & Prof#=Long Branch Trib,Reach-1,1
Up Type=0
Dn Type=3
Dn Slope=0.005
Boundary for River Rch & Prof#=Long Branch Trib,Reach-1,2
Up Type=0
Dn Type=3
Dn Slope=0.005
Boundary for River Rch & Prof#=Long Branch Trib,Reach-1,3
Up Type=0
Dn Type=3
Dn Slope=0.005
Boundary for River Rch & Prof#=Long Branch Trib,Reach-1,4
Up Type=0
Dn Type=3
Dn Slope=0.005
Boundary for River Rch & Prof#=Long Branch Trib,Reach-1,5
Up Type=0
Dn Type=3
Dn Slope=0.005
Boundary for River Rch & Prof#=Long Branch Trib,Reach-1,6
Up Type=0
Dn Type=3
Dn Slope=0.005
Boundary for River Rch & Prof#=Long Branch Trib,Reach-1,7
Up Type=0
Dn Type=3
Dn Slope=0.005

--- Long Branch Trib4.g01 (geometry) ---

Geom Title=Existing Conditions

River Reach=Long Branch Trib,Reach-1
Reach XY= 30
      1366355.00      6843188.00      1366414.79      6843198.52
      1366605.00      6843380.93      1366752.70      6843243.83
      1366961.17      6843180.14      1367149.89      6842990.29
      1367112.56      6842888.00      1367160.82      6842785.72
      1367260.62      6842643.62      1367396.86      6842544.07
      1367527.99      6842264.48      1367610.84      6842190.05
      1367803.45      6842184.25      1368011.07      6842079.87
      1368091.38      6842001.24      1368197.70      6841838.08
      1368113.24      6841691.23      1368147.20      6841638.10
      1368107.47      6841582.51      1368106.91      6841493.72
      1368199.38      6841432.38      1368255.13      6841315.32
      1368252.66      6841193.52      1368156.36      6841028.35
      1368157.16      6840843.43      1368252.56      6840743.52
      1368349.03      6840735.67      1368461.06      6840679.86
      1368632.14      6840511.53      1368655.00      6840338.00

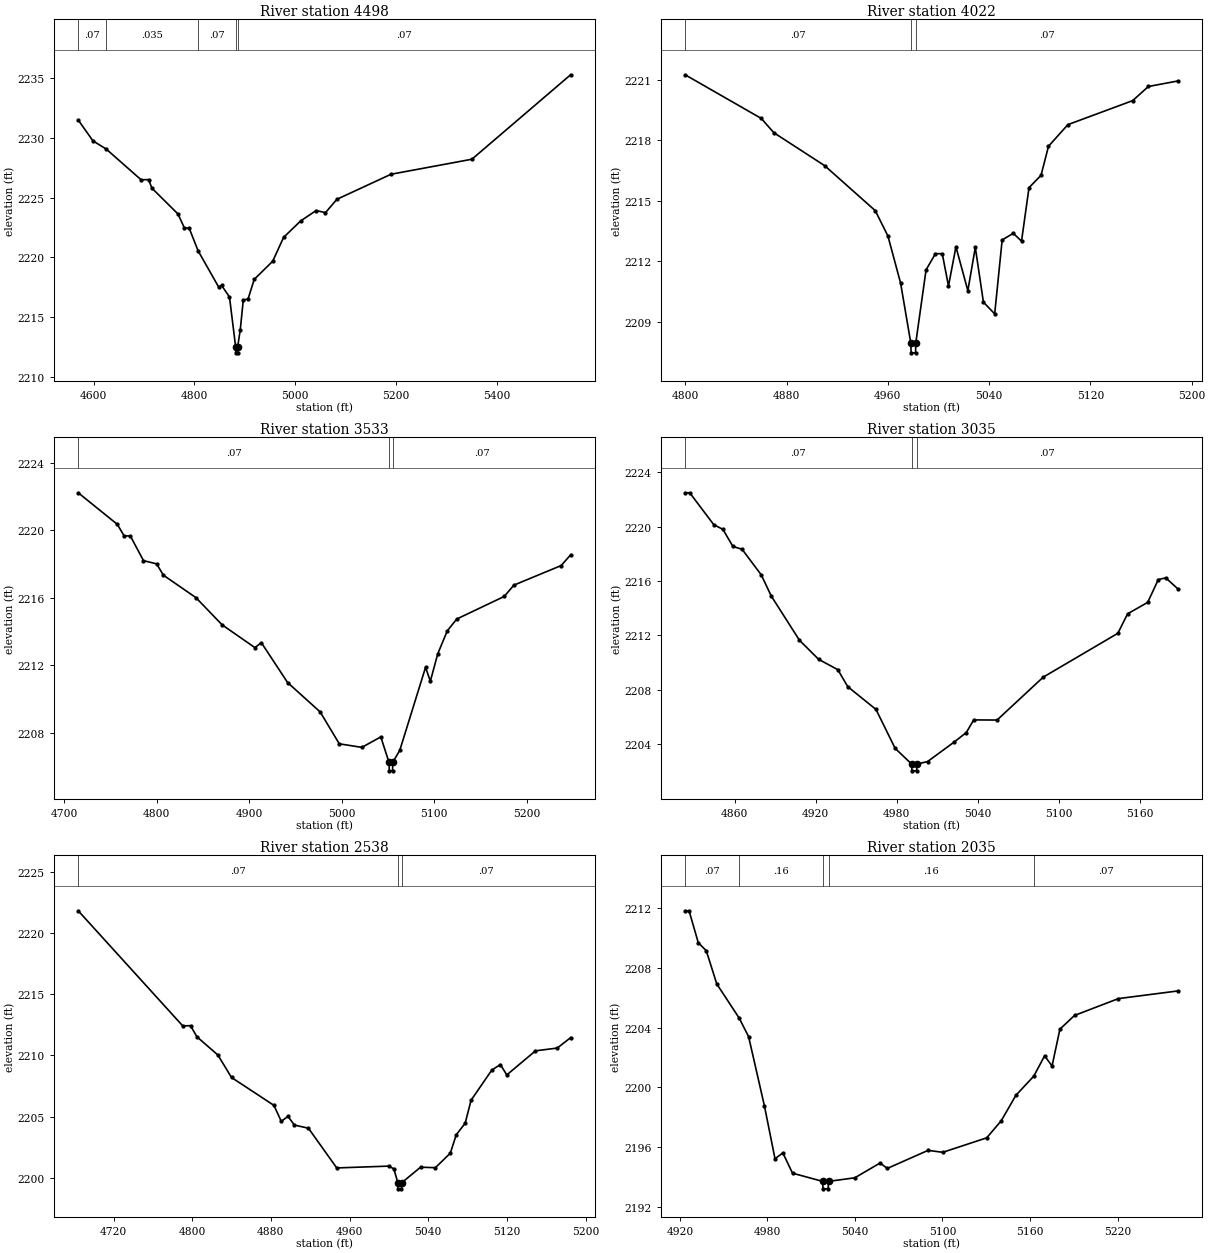
Type RM Length L Ch R = 1,4498,476,476,476
BEGIN DESCRIPTION:
Long Branch Trib4 7.0
END DESCRIPTION:
XS GIS Cut Line= 3
      1366754.99      6843687.98      1366535.00      6843318.16
      1366404.99      6842787.97
#Sta/Elev= 30
  4569.7 2231.51  4598.9 2229.76  4625.3 2229.07  4694.3 2226.50  4709.3 2226.51
  4715.7 2225.80  4767.5 2223.63  4780.0 2222.48  4789.8 2222.43  4807.3 2220.55
  4848.2 2217.50  4854.0 2217.64  4869.6 2216.67  4881.8 2212.49  4882.1 2211.99
  4885.6 2211.99  4885.8 2212.49  4891.0 2213.93  4896.9 2216.39  4906.6 2216.53
  4918.7 2218.15  4955.3 2219.67  4976.9 2221.67  5010.5 2223.04  5041.4 2223.92
  5059.9 2223.74  5082.5 2224.86  5189.8 2226.96  5350.2 2228.22  5545.9 2235.30
#Mann=5,-1,0
  4569.7    0.07       0  4625.3   0.035       0  4807.3    0.07       0
  4881.8    0.07       0  4885.8    0.07       0
Bank Sta=4881.8,4885.8
Exp/Cntr=0.3,0.1

Type RM Length L Ch R = 1,4022,489,489,489
BEGIN DESCRIPTION:
Long Branch Trib4 6.0
END DESCRIPTION:
XS GIS Cut Line= 3
      1366905.00      6843388.02      1366915.07      6843188.17
      1366755.03      6843088.02
#Sta/Elev= 30
  4799.9 2221.24  4860.0 2219.08  4870.0 2218.37  4910.1 2216.74  4950.1 2214.51
  4960.1 2213.25  4970.1 2210.92  4978.1 2207.97  4978.4 2207.47  4981.9 2207.47
  4982.1 2207.97  4990.2 2211.58  4997.6 2212.38  5003.0 2212.38  5007.9 2210.78
  5013.8 2212.72  5023.2 2210.55  5029.1 2212.69  5035.5 2209.98  5044.4 2209.40
  5050.3 2213.06  5059.1 2213.39  5065.6 2213.00  5071.5 2215.65  5081.0 2216.26
  5086.9 2217.70  5102.2 2218.77  5153.4 2219.96  5165.8 2220.66  5188.8 2220.93
#Mann=3,-1,0
  4799.9    0.07       0  4978.1    0.07       0  4982.1    0.07       0
Bank Sta=4978.1,4982.1
Exp/Cntr=0.3,0.1

Type RM Length L Ch R = 1,3533,498,498,498
BEGIN DESCRIPTION:
Long Branch Trib4 5.0
END DESCRIPTION:
XS GIS Cut Line= 3
      1367355.01      6843038.01      1367146.20      6842844.04
      1366905.02      6842788.01
#Sta/Elev= 30
  4715.0 2222.21  4757.3 2220.34  4764.6 2219.66  4771.4 2219.65  4785.6 2218.19
  4799.8 2218.00  4807.1 2217.33  4842.3 2216.00  4870.6 2214.39  4906.1 2213.04
  4913.1 2213.33  4941.5 2210.97  4976.7 2209.23  4997.4 2207.34  5021.8 2207.13
  5042.3 2207.75  5051.2 2206.24  5051.5 2205.74  5055.0 2205.74  5055.2 2206.24
  5062.8 2206.95  5090.7 2211.87  5095.9 2211.05  5103.9 2212.67  5114.2 2214.03
  5124.4 2214.73  5175.8 2216.07  5186.3 2216.74  5237.4 2217.90  5247.6 2218.53
#Mann=3,-1,0
  4715.0    0.07       0  5051.2    0.07       0  5055.2    0.07       0
Bank Sta=5051.2,5055.2
Exp/Cntr=0.3,0.1

Type RM Length L Ch R = 1,3035,497,497,497
BEGIN DESCRIPTION:
Long Branch Trib4 4.0
END DESCRIPTION:
XS GIS Cut Line= 3
      1367554.97      6842587.98      1367425.18      6842468.07
      1367254.98      6842387.99
#Sta/Elev= 30
  4823.3 2222.48  4826.7 2222.48  4844.5 2220.14  4851.3 2219.79  4858.7 2218.54
  4865.5 2218.33  4879.7 2216.45  4887.1 2214.90  4908.0 2211.65  4922.2 2210.25
  4936.4 2209.49  4943.8 2208.24  4964.7 2206.57  4978.9 2203.71  4991.1 2202.56
  4991.3 2202.06  4994.8 2202.06  4995.1 2202.56  5002.9 2202.74  5022.3 2204.15
  5031.6 2204.87  5037.1 2205.80  5054.4 2205.79  5088.6 2208.94  5143.9 2212.16
  5151.1 2213.59  5166.0 2214.43  5173.9 2216.11  5179.4 2216.23  5188.1 2215.45
#Mann=3,-1,0
  4823.3    0.07       0  4991.1    0.07       0  4995.1    0.07       0
Bank Sta=4991.1,4995.1
Exp/Cntr=0.3,0.1

Type RM Length L Ch R = 1,2538,503,503,503
BEGIN DESCRIPTION:
Long Branch Trib4 3.0
END DESCRIPTION:
XS GIS Cut Line= 3
      1368005.04      6842388.03      1367760.18      6842188.44
      1367605.04      6842088.03
#Sta/Elev= 30
  4684.1 2221.84  4790.4 2212.42  4798.3 2212.44  4804.8 2211.53  4826.1 2210.04
  4840.0 2208.20  4883.1 2205.92  4890.6 2204.61  4897.4 2205.02  4903.9 2204.31
  4918.2 2204.05  4947.0 2200.80  5000.0 2200.95  5005.1 2200.72  5009.1 2199.59
  5009.3 2199.09  5012.8 2199.09  5013.1 2199.59  5032.2 2200.86  5047.3 2200.82
  5062.5 2202.01  5068.5 2203.51  5077.6 2204.46  5083.6 2206.34  5104.7 2208.81
  5113.4 2209.26  5119.9 2208.41  5149.1 2210.38  5171.3 2210.61  5184.8 2211.46
#Mann=3,-1,0
  4684.1    0.07       0  5009.1    0.07       0  5013.1    0.07       0
Bank Sta=5009.1,5013.1
Exp/Cntr=0.3,0.1

Type RM Length L Ch R = 1,2035,191,191,191
BEGIN DESCRIPTION:
Long Branch Trib4 2.0
END DESCRIPTION:
XS GIS Cut Line= 3
      1368204.98      6841937.99      1368134.78      6841907.84
      1367874.66      6841930.50
#Sta/Elev= 30
  4923.6 2211.84  4926.3 2211.84  4932.6 2209.70  4938.1 2209.16  4945.3 2206.93
  4960.6 2204.65  4967.1 2203.40  4978.0 2198.73  4985.2 2195.21  4990.6 2195.60
  4997.2 2194.24  5017.9 2193.69  5018.1 2193.19  5021.6 2193.19  5021.9 2193.69
  5039.9 2193.93  5057.2 2194.92  5062.2 2194.56  5090.1 2195.77  5100.2 2195.64
  5130.3 2196.61  5140.3 2197.76  5150.3 2199.46  5162.6 2200.75  5170.0 2202.11
  5175.1 2201.43  5180.5 2203.90  5190.5 2204.82  5220.6 2205.95  5261.1 2206.46
#Mann=5,-1,0
  4923.6    0.07       0  4960.6    0.16       0  5017.9    0.07       0
  5021.9    0.16       0  5162.6    0.07       0
Bank Sta=5017.9,5021.9
Exp/Cntr=0.3,0.1

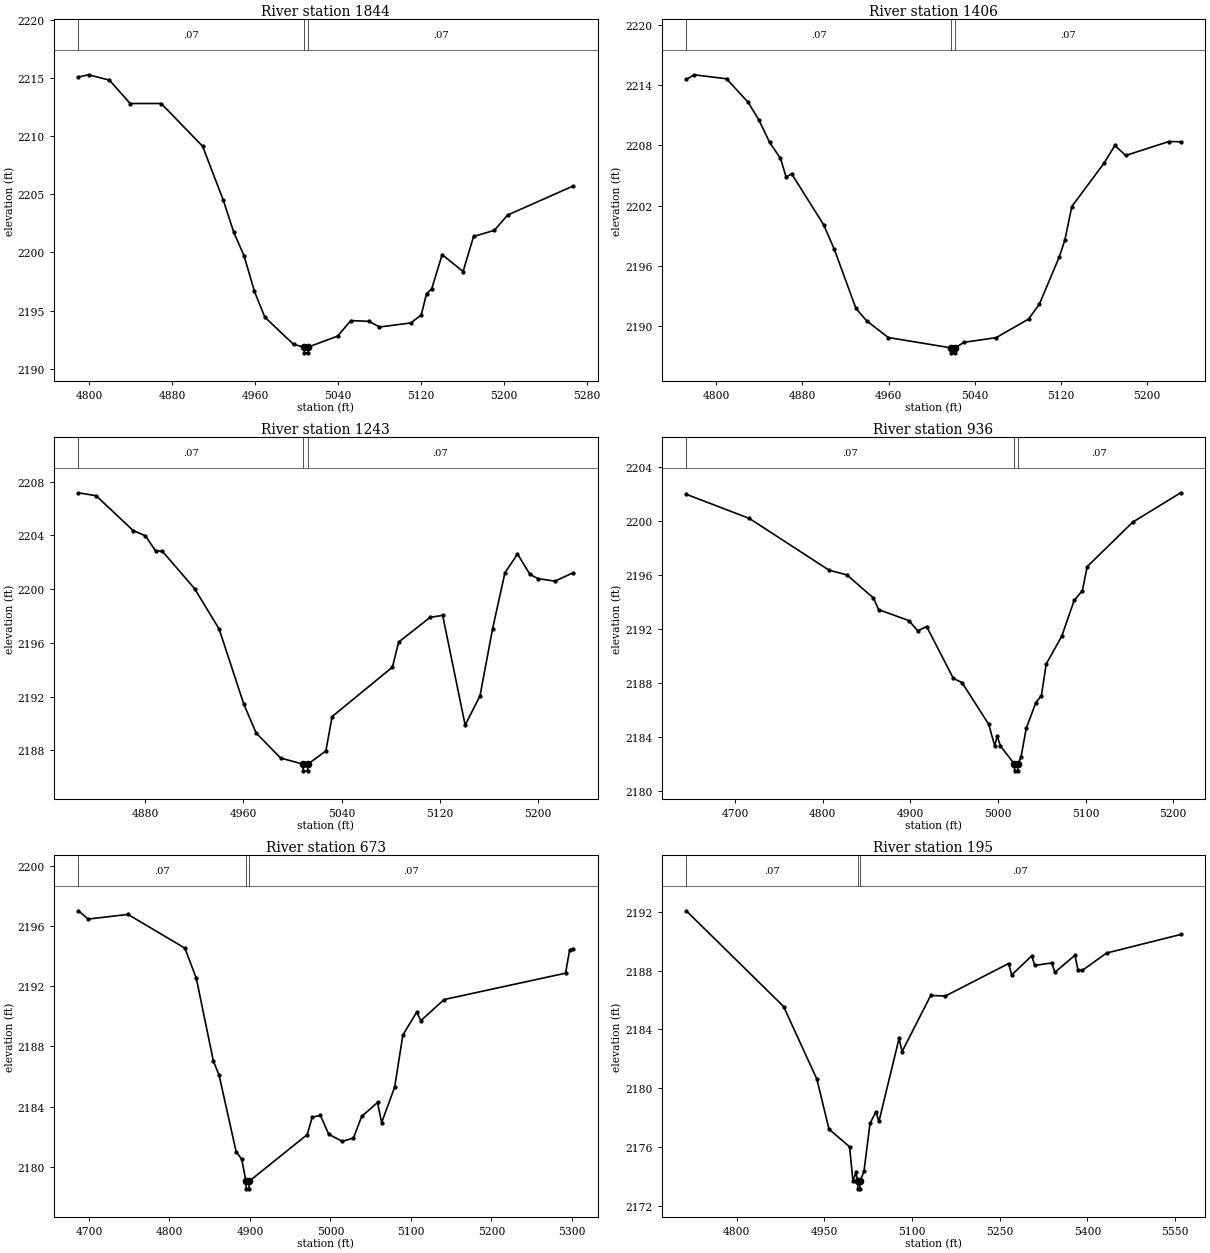
Type RM Length L Ch R = 1,1844,438,438,438
BEGIN DESCRIPTION:
Long Branch Trib4 1.1
END DESCRIPTION:
XS GIS Cut Line= 3
      1368364.85      6841755.18      1368154.35      6841756.41
      1367889.89      6841791.67
#Sta/Elev= 30
  4789.5 2215.08  4799.3 2215.27  4819.4 2214.81  4839.4 2212.80  4869.4 2212.80
  4909.4 2209.12  4929.4 2204.47  4939.4 2201.74  4949.4 2199.70  4959.4 2196.65
  4969.4 2194.44  4997.2 2192.09  5007.4 2191.87  5007.7 2191.37  5011.2 2191.37
  5011.4 2191.87  5039.7 2192.81  5052.4 2194.14  5070.0 2194.08  5080.1 2193.59
  5110.3 2193.94  5120.4 2194.62  5125.5 2196.45  5130.5 2196.87  5140.6 2199.81
  5160.8 2198.36  5170.9 2201.37  5191.0 2201.90  5203.7 2203.21  5266.8 2205.70
#Mann=3,-1,0
  4789.5    0.07       0  5007.4    0.07       0  5011.4    0.07       0
Bank Sta=5007.4,5011.4
Exp/Cntr=0.3,0.1

Type RM Length L Ch R = 1,1406,163,163,163
BEGIN DESCRIPTION:
Long Branch Trib4 1.0
END DESCRIPTION:
XS GIS Cut Line= 3
      1368432.31      6841428.40      1368204.89      6841415.20
      1367974.06      6841429.96
#Sta/Elev= 30
  4772.2 2214.59  4779.5 2215.06  4809.6 2214.66  4829.6 2212.32  4839.6 2210.55
  4849.6 2208.31  4859.7 2206.71  4865.0 2204.83  4870.0 2205.18  4899.7 2200.09
  4909.7 2197.62  4929.8 2191.71  4939.8 2190.47  4959.8 2188.81  5017.9 2187.78
  5018.2 2187.28  5021.7 2187.28  5021.9 2187.78  5030.0 2188.33  5060.0 2188.80
  5090.1 2190.66  5100.1 2192.15  5118.7 2196.90  5123.7 2198.53  5130.2 2201.90
  5160.2 2206.24  5170.2 2208.00  5180.3 2207.00  5220.3 2208.39  5231.3 2208.37
#Mann=3,-1,0
  4772.2    0.07       0  5017.9    0.07       0  5021.9    0.07       0
Bank Sta=5017.9,5021.9
Exp/Cntr=0.3,0.1

Type RM Length L Ch R = 1,1243,307,307,307
BEGIN DESCRIPTION:
Long Branch Trib4 2736
END DESCRIPTION:
XS GIS Cut Line= 3
      1368429.42      6841276.07      1368255.41      6841268.03
      1368030.58      6841307.69
#Sta/Elev= 30
  4825.8 2207.18  4840.2 2206.96  4870.3 2204.37  4880.3 2203.98  4888.8 2202.83
  4893.8 2202.86  4920.3 2200.05  4940.3 2197.04  4960.4 2191.45  4970.4 2189.30
  4990.4 2187.43  5008.6 2186.98  5008.8 2186.48  5012.3 2186.48  5012.6 2186.98
  5027.2 2187.96  5032.3 2190.52  5081.4 2194.20  5086.4 2196.06  5112.1 2197.91
  5122.3 2198.05  5140.6 2189.88  5152.7 2192.07  5162.9 2197.05  5173.0 2201.23
  5183.2 2202.62  5193.3 2201.11  5199.9 2200.79  5213.7 2200.60  5228.3 2201.22
#Mann=3,-1,0
  4825.8    0.07       0  5008.6    0.07       0  5012.6    0.07       0
Bank Sta=5008.6,5012.6
Exp/Cntr=0.3,0.1

Type RM Length L Ch R = 1,936,263,263,263
BEGIN DESCRIPTION:
Long Branch Trib4 4183
END DESCRIPTION:
XS GIS Cut Line= 3
      1368506.23      6841046.10      1368154.55      6840992.73
      1367963.62      6841076.48
#Sta/Elev= 30
  4644.3 2202.01  4716.3 2200.22  4807.4 2196.38  4827.6 2196.04  4857.9 2194.32
  4863.9 2193.46  4898.4 2192.65  4908.5 2191.89  4918.6 2192.21  4949.0 2188.38
  4959.1 2188.05  4989.4 2184.97  4996.3 2183.37  4999.1 2184.09  5002.8 2183.37
  5018.7 2182.02  5019.0 2181.52  5022.5 2181.52  5022.7 2182.02  5026.2 2182.51
  5032.3 2184.68  5043.2 2186.57  5049.6 2187.10  5055.0 2189.43  5072.9 2191.51
  5086.9 2194.14  5096.3 2194.86  5101.8 2196.65  5153.9 2199.95  5208.5 2202.12
#Mann=3,-1,0
  4644.3    0.07       0  5018.7    0.07       0  5022.7    0.07       0
Bank Sta=5018.7,5022.7
Exp/Cntr=0.3,0.1

Type RM Length L Ch R = 1,673,478,478,478
BEGIN DESCRIPTION:
Long Branch Trib4 4184
END DESCRIPTION:
XS GIS Cut Line= 3
      1368480.16      6840889.86      1368330.00      6840738.00
      1367938.81      6840824.47
#Sta/Elev= 30
  4687.0 2197.00  4699.1 2196.45  4748.5 2196.76  4819.2 2194.52  4833.4 2192.52
  4854.6 2187.03  4861.7 2186.09  4882.9 2181.01  4889.9 2180.51  4895.0 2179.05
  4895.3 2178.55  4898.8 2178.55  4899.0 2179.05  4971.2 2182.15  4977.4 2183.31
  4987.6 2183.42  4997.9 2182.17  5014.8 2181.70  5028.6 2181.92  5038.8 2183.35
  5058.5 2184.28  5063.6 2182.94  5079.8 2185.30  5090.0 2188.76  5107.2 2190.28
  5112.4 2189.71  5141.2 2191.11  5292.1 2192.86  5297.2 2194.41  5301.2 2194.48
#Mann=3,-1,0
  4687.0    0.07       0  4895.0    0.07       0  4899.0    0.07       0
Bank Sta=4895,4899
Exp/Cntr=0.3,0.1

Type RM Length L Ch R = 1,195,0,0,0
BEGIN DESCRIPTION:
Long Branch Trib4 4185
END DESCRIPTION:
XS GIS Cut Line= 3
      1368814.33      6840733.58      1368622.13      6840521.52
      1368082.77      6840670.29
#Sta/Elev= 30
  4713.8 2192.06  4880.3 2185.56  4937.1 2180.64  4958.0 2177.23  4993.1 2176.04
  4999.0 2173.68  5003.9 2174.29  5007.1 2173.68  5007.3 2173.18  5010.8 2173.18
  5011.1 2173.68  5017.8 2174.38  5028.1 2177.62  5038.2 2178.41  5043.4 2177.76
  5077.8 2183.39  5083.0 2182.50  5131.9 2186.31  5156.9 2186.27  5265.2 2188.48
  5270.4 2187.70  5304.7 2189.00  5309.9 2188.35  5339.1 2188.52  5344.3 2187.88
  5378.6 2189.04  5383.8 2188.04  5391.2 2188.01  5432.7 2189.19  5559.5 2190.45
#Mann=3,-1,0
  4713.8    0.07       0  5007.1    0.07       0  5011.1    0.07       0
Bank Sta=5007.1,5011.1
Exp/Cntr=0.3,0.1

Chan Stop Cuts=-1