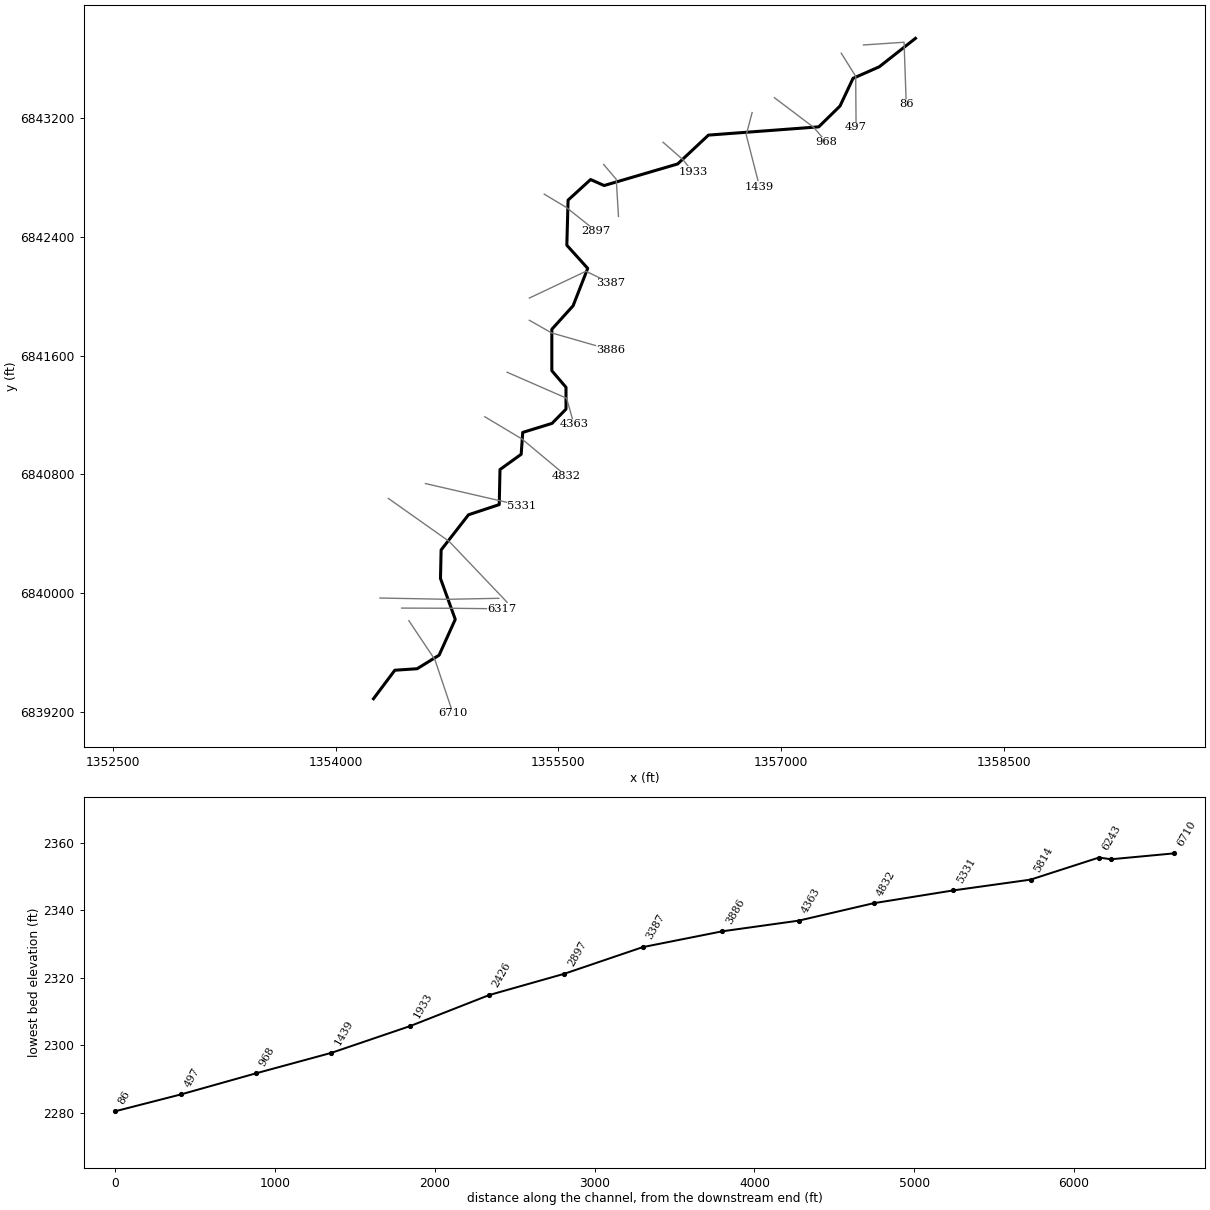
--- Oak Spring.prj (project) ---

Proj Title=Oak Spring Base Level Engineering
Current Plan=p01
Default Exp/Contr=0.3,0.1
English Units
Geom File=g01
Flow File=f01
Plan File=p01
Y Axis Title=Elevation
X Axis Title(PF)=Main Channel Distance
X Axis Title(XS)=Station
BEGIN DESCRIPTION:
Oak Spring
END DESCRIPTION:
DSS Export Rating Curves= 0
DSS Export Rating Curve Sorted= 0
DSS Export Volume Flow Curves= 0
DXF OffsetX= 0
DXF OffsetY= 0
DXF ScaleX= 1
DXF ScaleY= 10

--- Oak Spring.p01 (plan) ---

Plan Title=Multiple Run
Short Identifier=Multiple
Geom File=g01
Flow File=f01
Subcritical Flow
K Sum by GR= 0
Std Step Tol= 0.01
Critical Tol= 0.01
Num of Std Step Trials= 20
Max Error Tol= 0.3
Flow Tol Ratio= 0.001
Split Flow NTrial= 30
Split Flow Tol= 0.02
Split Flow Ratio= 0.02
Log Output Level= 0
Friction Slope Method= 1
Unsteady Friction Slope Method= 2
Unsteady Bridges Friction Slope Method= 1
Parabolic Critical Depth
Global Vel Dist=  1 , 1 , 1
Global Log Level= 0
CheckData=True
Encroach Param= -1, 0, 0, 0
BEGIN DESCRIPTION:
Multiple Run
END DESCRIPTION:

--- Oak Spring.f01 (steady flow) ---

Flow Title=Multiple
Program Version=4.10
Number of Profiles= 7
Profile Names=10-year,25-year,50-year,1pct_min,100-year,1pct_plu,500-year
River Rch & RM=Oak Spring,Reach-1         ,6710
     194     268     329     201     401     800     602
River Rch & RM=Oak Spring,Reach-1         ,6317
     335     482     607     379     757    1510    1195
Boundary for River Rch & Prof#=Oak Spring,Reach-1         , 1
Up Type= 0
Dn Type= 3
Dn Slope=0.012
Boundary for River Rch & Prof#=Oak Spring,Reach-1         , 2
Up Type= 0
Dn Type= 3
Dn Slope=0.012
Boundary for River Rch & Prof#=Oak Spring,Reach-1         , 3
Up Type= 0
Dn Type= 3
Dn Slope=0.012
Boundary for River Rch & Prof#=Oak Spring,Reach-1         , 4
Up Type= 0
Dn Type= 3
Dn Slope=0.012
Boundary for River Rch & Prof#=Oak Spring,Reach-1         , 5
Up Type= 0
Dn Type= 3
Dn Slope=0.012
Boundary for River Rch & Prof#=Oak Spring,Reach-1         , 6
Up Type= 0
Dn Type= 3
Dn Slope=0.012
Boundary for River Rch & Prof#=Oak Spring,Reach-1         , 7
Up Type= 0
Dn Type= 3
Dn Slope=0.012
DSS Import GetInterval= 0
DSS Import GetPeak= 0
DSS Import FillOption= 0

--- Oak Spring.g01 (geometry) ---

Geom Title=Existing Conditions

River Reach=Oak Spring,Reach-1
Reach XY= 30
      1354255.00      6839288.00      1354398.81      6839480.19
      1354549.07      6839490.25      1354696.98      6839581.66
      1354805.72      6839822.94      1354706.22      6840098.50
      1354710.46      6840290.45      1354894.90      6840527.61
      1355101.94      6840596.28      1355106.98      6840832.33
      1355249.63      6840935.31      1355260.18      6841082.59
      1355457.44      6841143.52      1355551.48      6841239.46
      1355551.46      6841386.53      1355456.06      6841498.44
      1355456.05      6841777.57      1355599.17      6841935.70
      1355697.69      6842188.10      1355557.06      6842343.85
      1355565.47      6842647.82      1355717.15      6842786.49
      1355808.27      6842746.11      1356303.50      6842891.61
      1356510.85      6843085.94      1357253.54      6843141.54
      1357396.86      6843281.94      1357484.52      6843468.38
      1357661.06      6843546.14      1357905.00      6843738.00

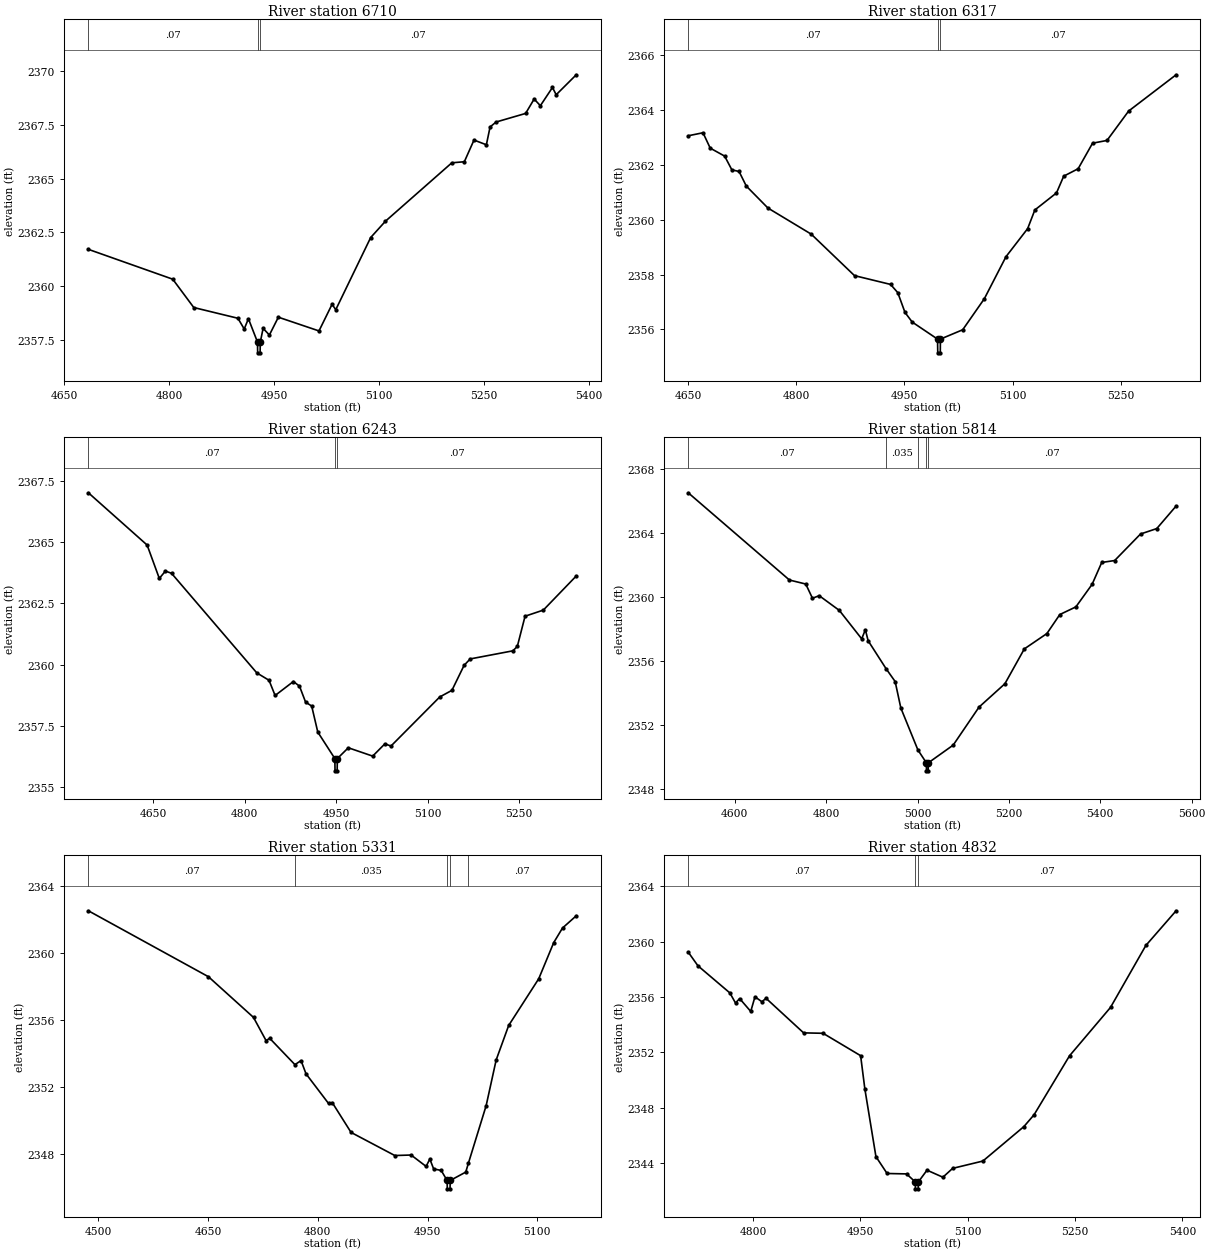
Type RM Length L Ch R = 1,6710,393,393,393
BEGIN DESCRIPTION:
Oak Spring 13.0
END DESCRIPTION:
XS GIS Cut Line= 3
      1354493.34      6839813.84      1354668.57      6839551.47
      1354790.37      6839189.41
#Sta/Elev= 30
  4684.5 2361.71  4805.1 2360.32  4835.2 2359.00  4898.3 2358.50  4907.3 2358.00
  4913.3 2358.48  4926.3 2357.39  4926.5 2356.89  4930.0 2356.89  4930.3 2357.39
  4934.3 2358.03  4943.3 2357.72  4956.1 2358.55  5014.2 2357.91  5032.9 2359.15
  5038.2 2358.90  5088.1 2362.26  5109.2 2363.02  5204.1 2365.74  5222.0 2365.79
  5235.8 2366.80  5253.5 2366.58  5258.8 2367.41  5267.4 2367.64  5309.6 2368.04
  5321.8 2368.71  5330.7 2368.40  5348.0 2369.25  5353.3 2368.91  5382.0 2369.84
#Mann=3,-1,0
  4684.5    0.07       0  4926.3    0.07       0  4930.3    0.07       0
Bank Sta=4926.3,4930.3
Exp/Cntr=0.3,0.1

Type RM Length L Ch R = 1,6317,74,74,74
BEGIN DESCRIPTION:
Oak Spring 12.0
END DESCRIPTION:
XS GIS Cut Line= 3
      1354444.50      6839898.88      1354794.19      6839897.63
      1355120.77      6839893.69
#Sta/Elev= 30
  4650.3 2363.05  4670.8 2363.16  4680.8 2362.60  4700.8 2362.31  4710.8 2361.81
  4720.8 2361.75  4730.8 2361.22  4760.8 2360.42  4820.8 2359.47  4880.8 2357.96
  4930.8 2357.64  4940.8 2357.34  4950.8 2356.62  4960.8 2356.27  4995.9 2355.65
  4996.2 2355.15  4999.7 2355.15  4999.9 2355.65  5030.8 2355.99  5060.8 2357.12
  5090.8 2358.65  5120.8 2359.67  5130.8 2360.35  5160.8 2360.97  5170.8 2361.58
  5190.8 2361.85  5210.8 2362.78  5230.8 2362.88  5260.8 2363.95  5326.6 2365.27
#Mann=3,-1,0
  4650.3    0.07       0  4995.9    0.07       0  4999.9    0.07       0
Bank Sta=4995.9,4999.9
Exp/Cntr=0.3,0.1

Type RM Length L Ch R = 1,6243,429,429,429
BEGIN DESCRIPTION:
Oak Spring 4235
END DESCRIPTION:
XS GIS Cut Line= 3
      1354298.62      6839966.59      1354755.24      6839958.10
      1355098.98      6839964.86
#Sta/Elev= 30
  4543.3 2367.00  4639.7 2364.87  4659.7 2363.51  4669.7 2363.81  4679.7 2363.72
  4819.7 2359.66  4839.7 2359.36  4849.7 2358.74  4879.7 2359.31  4889.7 2359.12
  4899.7 2358.47  4909.7 2358.31  4919.7 2357.25  4947.7 2356.17  4948.0 2355.67
  4951.5 2355.67  4951.8 2356.17  4969.8 2356.61  5009.8 2356.27  5029.8 2356.77
  5039.8 2356.68  5119.8 2358.68  5139.8 2358.95  5159.8 2359.97  5169.8 2360.23
  5239.8 2360.56  5247.1 2360.74  5259.8 2361.97  5289.8 2362.22  5343.8 2363.61
#Mann=3,-1,0
  4543.3    0.07       0  4947.7    0.07       0  4951.8    0.07       0
Bank Sta=4947.7,4951.8
Exp/Cntr=0.3,0.1

Type RM Length L Ch R = 1,5814,483,483,483
BEGIN DESCRIPTION:
Oak Spring 11.0
END DESCRIPTION:
XS GIS Cut Line= 3
      1354354.97      6840638.02      1354764.88      6840348.05
      1355155.01      6839937.99
#Sta/Elev= 30
  4497.9 2366.51  4719.5 2361.05  4755.2 2360.80  4769.9 2359.91  4784.7 2360.07
  4828.7 2359.15  4877.7 2357.37  4885.7 2357.94  4891.8 2357.25  4931.1 2355.50
  4950.9 2354.70  4963.4 2353.04  5000.7 2350.42  5019.3 2349.61  5019.5 2349.11
  5023.2 2349.11  5023.5 2349.61  5078.0 2350.72  5134.6 2353.10  5191.2 2354.56
  5233.7 2356.74  5283.1 2357.70  5311.4 2358.89  5346.6 2359.37  5382.1 2360.78
  5403.2 2362.15  5431.5 2362.27  5488.1 2363.93  5523.7 2364.27  5566.0 2365.68
#Mann=5,-1,0
  4497.9    0.07       0  4931.1   0.035       0  5000.7    0.07       0
  5019.3   0.035       0  5023.5    0.07       0
Bank Sta=5019.3,5023.5
Exp/Cntr=0.3,0.1

Type RM Length L Ch R = 1,5331,499,499,499
BEGIN DESCRIPTION:
Oak Spring 10.0
END DESCRIPTION:
XS GIS Cut Line= 3
      1354605.00      6840738.00      1355105.64      6840622.44
      1355255.02      6840588.00
#Sta/Elev= 30
  4486.2 2362.53  4650.4 2358.59  4712.0 2356.16  4729.1 2354.78  4734.2 2354.91
  4768.6 2353.34  4777.0 2353.58  4783.8 2352.79  4814.6 2351.02  4819.7 2351.07
  4845.4 2349.29  4905.2 2347.91  4927.5 2347.94  4948.0 2347.26  4953.1 2347.70
  4958.3 2347.11  4968.6 2347.02  4976.7 2346.42  4977.0 2345.92  4980.7 2345.92
  4981.0 2346.42  5002.2 2346.92  5005.9 2347.46  5030.1 2350.89  5043.8 2353.62
  5060.9 2355.68  5102.0 2358.47  5122.5 2360.63  5134.5 2361.50  5153.3 2362.23
#Mann=5,-1,0
  4486.2    0.07       0  4768.6   0.035       0  4976.7   0.035       0
  4981.0   0.035       0  5005.9    0.07       0
Bank Sta=4976.7,4981
Exp/Cntr=0.3,0.1

Type RM Length L Ch R = 1,4832,469,469,469
BEGIN DESCRIPTION:
Oak Spring 9.0
END DESCRIPTION:
XS GIS Cut Line= 3
      1355005.04      6841187.98      1355254.49      6841038.51
      1355554.98      6840788.02
#Sta/Elev= 30
  4709.2 2359.24  4722.8 2358.25  4767.4 2356.29  4775.3 2355.56  4781.1 2355.88
  4796.6 2354.95  4802.5 2356.01  4812.2 2355.65  4818.0 2355.90  4870.5 2353.40
  4897.7 2353.37  4950.2 2351.75  4956.1 2349.35  4971.6 2344.45  4987.2 2343.23
  5014.4 2343.20  5026.6 2342.62  5026.9 2342.12  5030.6 2342.12  5030.9 2342.62
  5043.0 2343.47  5065.2 2342.96  5078.8 2343.60  5121.1 2344.13  5178.4 2346.62
  5192.7 2347.48  5242.2 2351.74  5299.5 2355.24  5348.9 2359.72  5391.2 2362.23
#Mann=3,-1,0
  4709.2    0.07       0  5026.6    0.07       0  5030.9    0.07       0
Bank Sta=5026.6,5030.9
Exp/Cntr=0.3,0.1

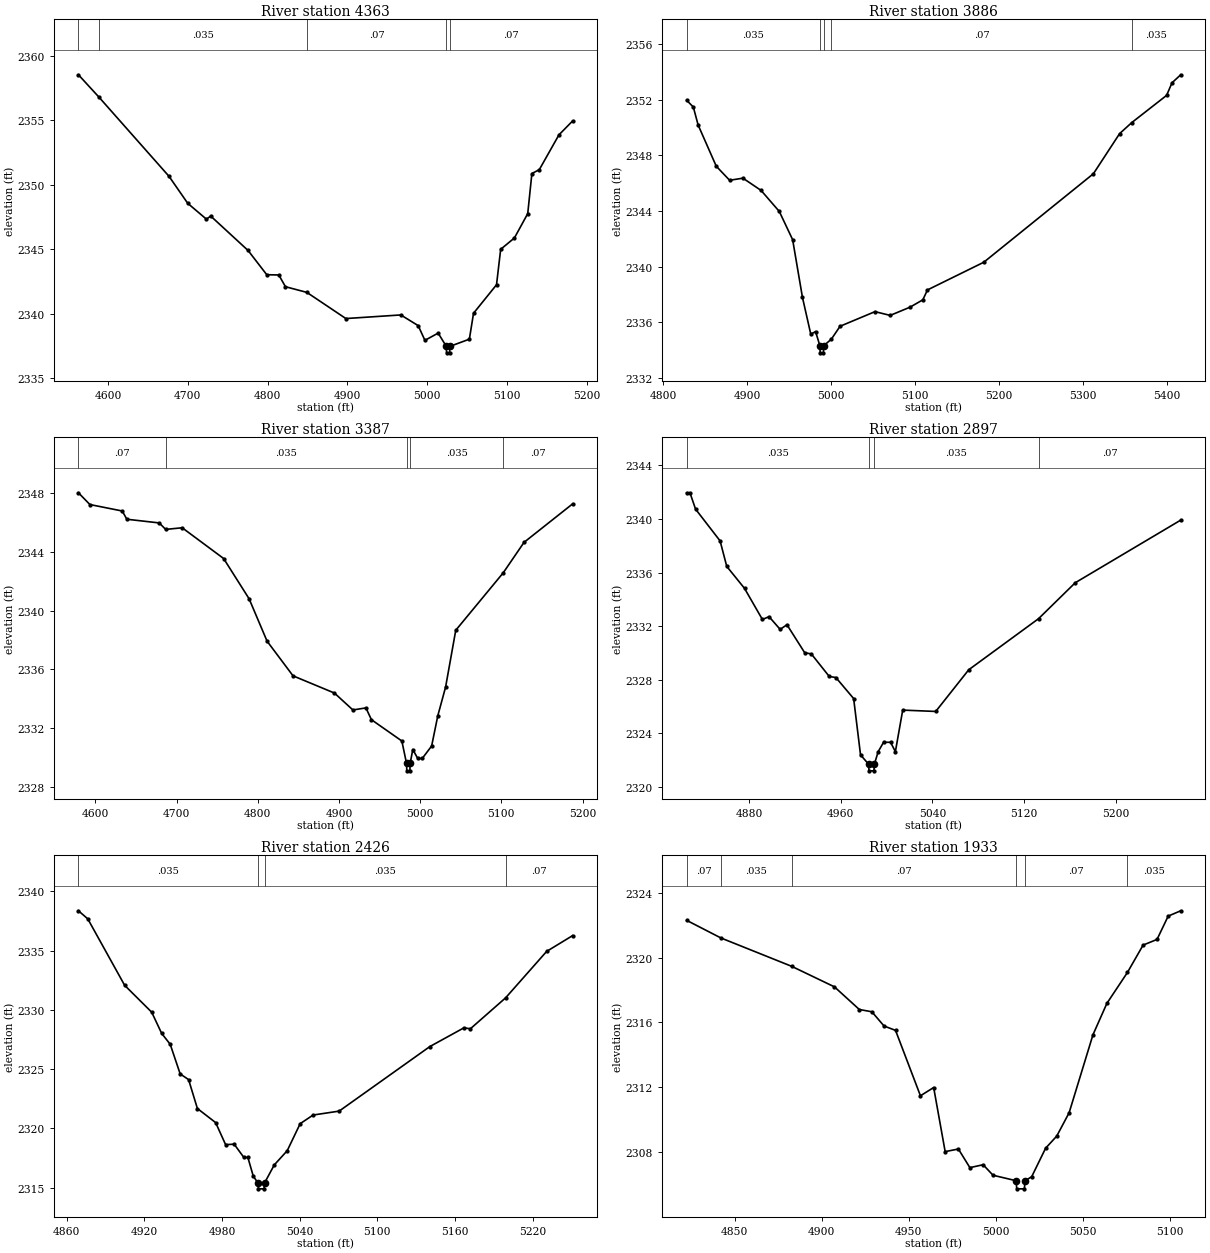
Type RM Length L Ch R = 1,4363,477,477,477
BEGIN DESCRIPTION:
Oak Spring 8.0
END DESCRIPTION:
XS GIS Cut Line= 3
      1355154.99      6841488.00      1355555.42      6841313.00
      1355605.00      6841137.99
#Sta/Elev= 30
  4563.0 2358.52  4588.5 2356.80  4676.5 2350.64  4699.9 2348.55  4723.3 2347.32
  4728.7 2347.56  4775.5 2344.89  4798.9 2343.01  4814.0 2342.99  4822.3 2342.08
  4849.1 2341.64  4898.0 2339.61  4966.8 2339.89  4988.6 2339.06  4997.0 2337.92
  5013.6 2338.48  5023.8 2337.45  5024.1 2336.95  5027.9 2336.95  5028.2 2337.45
  5052.7 2338.01  5057.9 2340.02  5086.7 2342.23  5091.9 2344.98  5109.1 2345.86
  5125.8 2347.75  5131.0 2350.86  5140.3 2351.16  5164.9 2353.86  5181.9 2354.93
#Mann=5,-1,0
  4563.0    0.07       0  4588.5   0.035       0  4849.1    0.07       0
  5023.8    0.07       0  5028.2    0.07       0
Bank Sta=5023.8,5028.2
Exp/Cntr=0.3,0.1

Type RM Length L Ch R = 1,3886,499,499,499
BEGIN DESCRIPTION:
Oak Spring 7.0
END DESCRIPTION:
XS GIS Cut Line= 3
      1355304.98      6841838.01      1355454.51      6841753.20
      1355854.97      6841638.01
#Sta/Elev= 30
  4828.1 2351.95  4836.1 2351.46  4841.8 2350.17  4863.4 2347.21  4879.3 2346.20
  4895.2 2346.35  4916.8 2345.47  4938.5 2343.96  4954.4 2341.93  4966.1 2337.78
  4976.0 2335.14  4981.7 2335.33  4986.9 2334.30  4987.2 2333.80  4991.0 2333.80
  4991.3 2334.30  5000.6 2334.79  5010.9 2335.71  5052.5 2336.76  5070.6 2336.49
  5094.2 2337.08  5109.5 2337.61  5115.0 2338.32  5182.1 2340.31  5312.7 2346.67
  5343.9 2349.55  5358.3 2350.34  5399.9 2352.30  5406.3 2353.20  5416.7 2353.78
#Mann=5,-1,0
  4828.1   0.035       0  4986.9   0.035       0  4991.3   0.035       0
  5000.6    0.07       0  5358.3   0.035       0
Bank Sta=4986.9,4991.3
Exp/Cntr=0.3,0.1

Type RM Length L Ch R = 1,3387,490,490,490
BEGIN DESCRIPTION:
Oak Spring 6.0
END DESCRIPTION:
XS GIS Cut Line= 3
      1355305.04      6841988.02      1355685.31      6842168.20
      1355855.01      6842087.99
#Sta/Elev= 30
  4579.2 2348.01  4593.3 2347.21  4633.2 2346.77  4638.8 2346.21  4678.7 2345.96
  4686.6 2345.52  4707.0 2345.63  4758.0 2343.54  4789.4 2340.80  4811.5 2337.92
  4843.5 2335.56  4894.5 2334.39  4917.2 2333.24  4933.3 2333.38  4940.0 2332.58
  4977.5 2331.13  4983.3 2329.60  4983.6 2329.10  4987.4 2329.10  4987.7 2329.60
  4991.0 2330.55  4997.1 2329.94  5002.6 2329.94  5014.2 2330.79  5021.8 2332.85
  5031.4 2334.80  5043.9 2338.66  5102.4 2342.57  5128.0 2344.64  5187.7 2347.25
#Mann=5,-1,0
  4579.2    0.07       0  4686.6   0.035       0  4983.3   0.035       0
  4987.7   0.035       0  5102.4    0.07       0
Bank Sta=4983.3,4987.7
Exp/Cntr=0.3,0.1

Type RM Length L Ch R = 1,2897,471,471,471
BEGIN DESCRIPTION:
Oak Spring 5.0
END DESCRIPTION:
XS GIS Cut Line= 3
      1355404.99      6842688.00      1355554.50      6842598.21
      1355754.96      6842438.03
#Sta/Elev= 30
  4825.6 2341.95  4828.5 2341.95  4833.4 2340.73  4854.8 2338.36  4860.6 2336.46
  4876.1 2334.82  4891.7 2332.50  4897.5 2332.71  4907.2 2331.76  4913.1 2332.11
  4928.6 2330.02  4934.4 2329.93  4950.0 2328.25  4955.8 2328.17  4971.3 2326.60
  4977.3 2322.40  4984.3 2321.71  4984.7 2321.21  4989.0 2321.21  4989.4 2321.71
  4992.7 2322.64  4997.4 2323.34  5003.5 2323.34  5007.7 2322.64  5014.1 2325.74
  5042.9 2325.64  5071.7 2328.75  5132.6 2332.56  5164.6 2335.24  5256.6 2339.91
#Mann=4,-1,0
  4825.6   0.035       0  4984.3   0.035       0  4989.4   0.035       0
  5132.6    0.07       0
Bank Sta=4984.3,4989.4
Exp/Cntr=0.3,0.1

Type RM Length L Ch R = 1,2426,493,493,493
BEGIN DESCRIPTION:
Oak Spring 4.0
END DESCRIPTION:
XS GIS Cut Line= 3
      1355804.98      6842888.02      1355889.81      6842788.33
      1355905.00      6842537.99
#Sta/Elev= 30
  4869.1 2338.36  4876.3 2337.68  4904.8 2332.07  4925.7 2329.80  4933.4 2328.01
  4940.0 2327.09  4947.7 2324.59  4954.2 2324.11  4961.0 2321.67  4975.1 2320.48
  4982.8 2318.62  4989.4 2318.66  4996.9 2317.54  5000.0 2317.54  5004.2 2315.95
  5007.8 2315.39  5008.2 2314.89  5012.5 2314.89  5012.9 2315.39  5020.4 2316.91
  5030.4 2318.11  5040.4 2320.39  5050.4 2321.12  5070.5 2321.45  5140.6 2326.90
  5166.9 2328.48  5171.9 2328.40  5199.1 2331.01  5230.8 2334.93  5250.8 2336.26
#Mann=4,-1,0
  4869.1   0.035       0  5007.8   0.035       0  5012.9   0.035       0
  5199.1    0.07       0
Bank Sta=5007.8,5012.9
Exp/Cntr=0.3,0.1

Type RM Length L Ch R = 1,1933,494,494,494
BEGIN DESCRIPTION:
Oak Spring 3.0
END DESCRIPTION:
XS GIS Cut Line= 3
      1356205.01      6843037.99      1356338.52      6842920.88
      1356404.97      6842838.04
#Sta/Elev= 30
  4822.4 2322.31  4842.1 2321.22  4882.7 2319.47  4907.3 2318.20  4921.6 2316.80
  4928.8 2316.66  4935.8 2315.78  4942.4 2315.51  4956.7 2311.47  4964.3 2311.98
  4970.9 2308.02  4978.5 2308.18  4985.1 2307.03  4992.7 2307.21  4998.4 2306.56
  5011.7 2306.22  5012.0 2305.72  5016.4 2305.72  5016.8 2306.22  5020.6 2306.47
  5028.6 2308.23  5035.0 2308.98  5042.1 2310.42  5055.8 2315.24  5063.8 2317.18
  5075.6 2319.09  5084.6 2320.78  5092.6 2321.13  5099.0 2322.57  5106.2 2322.90
#Mann=6,-1,0
  4822.4    0.07       0  4842.1   0.035       0  4882.7    0.07       0
  5011.7    0.07       0  5016.8    0.07       0  5075.6   0.035       0
Bank Sta=5011.7,5016.8
Exp/Cntr=0.3,0.1

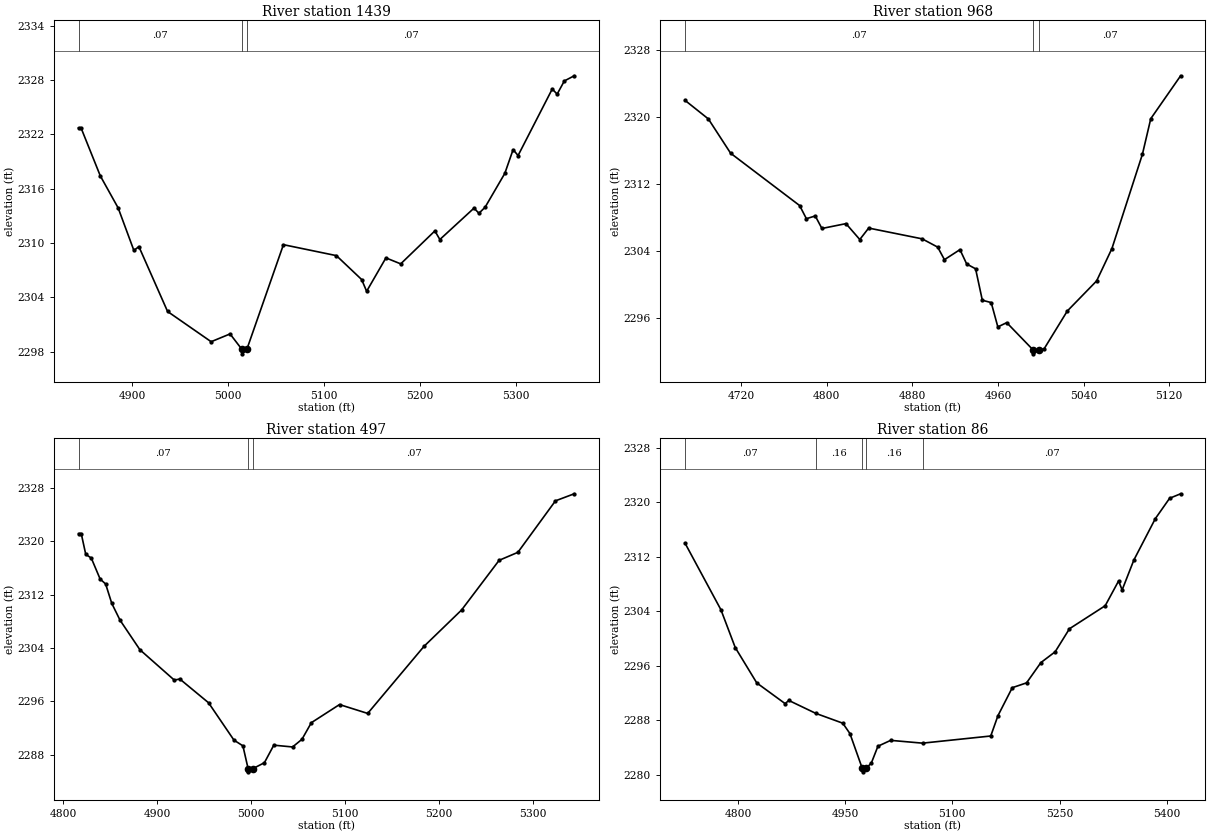
Type RM Length L Ch R = 1,1439,471,471,471
BEGIN DESCRIPTION:
Oak Spring 2.0
END DESCRIPTION:
XS GIS Cut Line= 3
      1356804.99      6843237.97      1356765.19      6843087.55
      1356855.00      6842738.00
#Sta/Elev= 30
  4844.4 2322.73  4847.0 2322.73  4867.1 2317.42  4885.7 2313.88  4902.1 2309.18
  4907.3 2309.61  4937.2 2302.44  4982.6 2299.10  5002.3 2299.96  5014.6 2298.26
  5015.0 2297.76  5019.8 2298.26  5057.9 2309.82  5113.1 2308.61  5139.4 2305.97
  5144.6 2304.67  5164.7 2308.36  5180.1 2307.70  5215.7 2311.34  5220.9 2310.39
  5256.5 2313.86  5261.6 2313.29  5268.0 2313.95  5288.6 2317.70  5297.2 2320.32
  5302.4 2319.67  5338.0 2327.02  5343.1 2326.45  5350.6 2327.91  5360.9 2328.48
#Mann=3,-1,0
  4844.4    0.07       0  5014.6    0.07       0  5019.8    0.07       0
Bank Sta=5014.6,5019.8
Exp/Cntr=0.3,0.1

Type RM Length L Ch R = 1,968,471,471,471
BEGIN DESCRIPTION:
Oak Spring 1.0
END DESCRIPTION:
XS GIS Cut Line= 3
      1356954.97      6843338.02      1357220.20      6843137.51
      1357304.98      6843038.03
#Sta/Elev= 30
  4667.5 2322.02  4689.4 2319.79  4710.2 2315.69  4774.7 2309.43  4781.0 2307.86
  4789.3 2308.19  4795.5 2306.69  4818.0 2307.27  4830.9 2305.37  4839.2 2306.74
  4889.2 2305.45  4903.7 2304.46  4910.0 2302.96  4924.5 2304.16  4930.8 2302.44
  4939.1 2301.87  4945.4 2298.11  4953.7 2297.83  4959.9 2294.92  4968.2 2295.43
  4992.6 2292.20  4993.0 2291.70  4998.0 2292.20  5003.0 2292.27  5024.8 2296.82
  5052.2 2300.42  5066.5 2304.29  5095.0 2315.57  5102.8 2319.82  5130.7 2324.95
#Mann=3,-1,0
  4667.5    0.07       0  4992.6    0.07       0  4998.0    0.07       0
Bank Sta=4992.6,4998
Exp/Cntr=0.3,0.1

Type RM Length L Ch R = 1,497,411,411,411
BEGIN DESCRIPTION:
Oak Spring 2207
END DESCRIPTION:
XS GIS Cut Line= 3
      1357405.00      6843637.99      1357502.45      6843482.27
      1357505.00      6843137.98
#Sta/Elev= 30
  4816.3 2321.16  4819.2 2321.16  4824.0 2318.05  4829.9 2317.49  4839.3 2314.35
  4845.2 2313.60  4851.7 2310.70  4860.5 2308.18  4881.7 2303.74  4918.3 2299.19
  4924.2 2299.35  4954.8 2295.79  4981.9 2290.18  4991.4 2289.33  4996.9 2285.93
  4997.3 2285.43  5002.3 2285.93  5014.3 2286.80  5024.3 2289.43  5044.3 2289.16
  5054.3 2290.31  5064.3 2292.80  5094.3 2295.52  5124.3 2294.19  5184.3 2304.25
  5224.3 2309.70  5264.3 2317.15  5284.3 2318.35  5324.3 2326.07  5344.3 2327.13
#Mann=3,-1,0
  4816.3    0.07       0  4996.9    0.07       0  5002.3    0.07       0
Bank Sta=4996.9,5002.3
Exp/Cntr=0.3,0.1

Type RM Length L Ch R = 1,86,0,0,0
BEGIN DESCRIPTION:
Oak Spring 4236
END DESCRIPTION:
XS GIS Cut Line= 3
      1357554.72      6843693.30      1357828.20      6843711.65
      1357842.92      6843292.61
#Sta/Elev= 30
  4725.9 2314.03  4776.3 2304.22  4796.3 2298.68  4826.4 2293.49  4866.1 2290.45
  4871.2 2290.92  4909.0 2289.02  4946.7 2287.58  4956.7 2286.06  4974.0 2280.94
  4974.4 2280.44  4979.5 2280.94  4986.8 2281.77  4995.9 2284.20  5013.7 2285.06
  5058.3 2284.65  5153.7 2285.70  5163.8 2288.69  5183.8 2292.79  5203.8 2293.50
  5223.8 2296.47  5243.8 2298.06  5263.8 2301.44  5313.8 2304.82  5332.5 2308.45
  5337.5 2307.14  5353.9 2311.53  5383.9 2317.60  5403.9 2320.59  5419.3 2321.25
#Mann=5,-1,0
  4725.9    0.07       0  4909.0    0.16       0  4974.0    0.07       0
  4979.5    0.16       0  5058.3    0.07       0
Bank Sta=4974,4979.5
Exp/Cntr=0.3,0.1

Chan Stop Cuts=-1