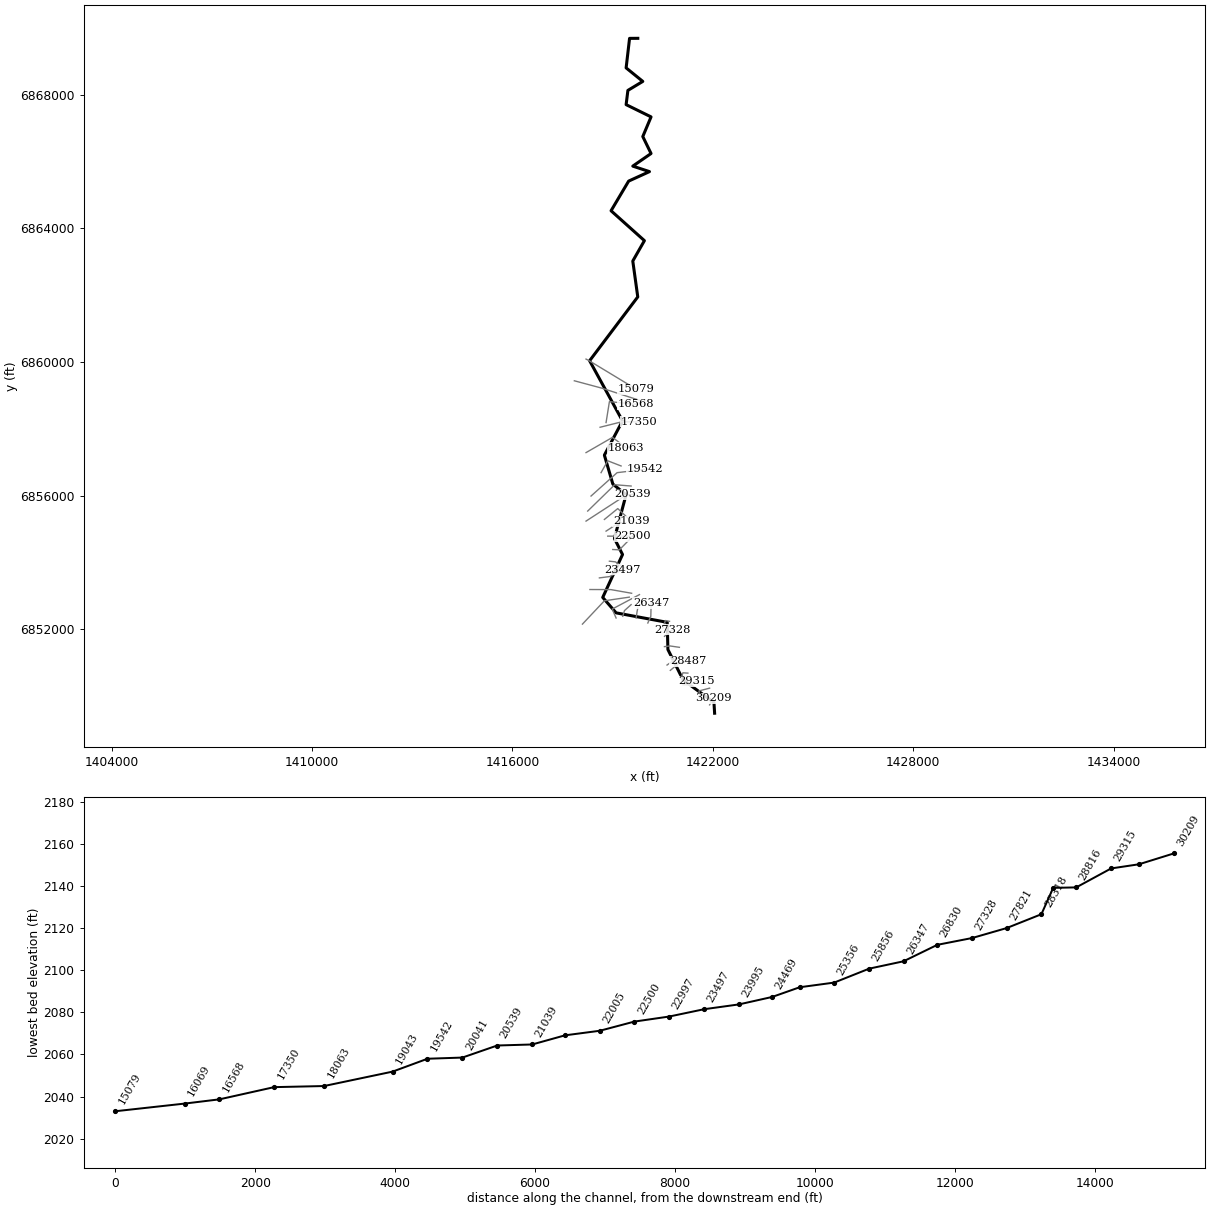
--- Plum Creek.prj (project) ---

Proj Title=Plum Creek Base Level Engineering
Current Plan=p01
Default Exp/Contr=0.3,0.1
English Units
Geom File=g01
Flow File=f01
Plan File=p01
Y Axis Title=Elevation
X Axis Title(PF)=Main Channel Distance
X Axis Title(XS)=Station
BEGIN DESCRIPTION:
Plum Creek
END DESCRIPTION:
DSS Export Rating Curves= 0
DSS Export Rating Curve Sorted= 0
DSS Export Volume Flow Curves= 0
DXF OffsetX= 0
DXF OffsetY= 0
DXF ScaleX= 1
DXF ScaleY= 10

--- Plum Creek.p01 (plan) ---

Plan Title=Multiple Run
Short Identifier=Multiple
Geom File=g01
Flow File=f01
Subcritical Flow
K Sum by GR= 0
Std Step Tol= 0.01
Critical Tol= 0.01
Num of Std Step Trials= 20
Max Error Tol= 0.3
Flow Tol Ratio= 0.001
Split Flow NTrial= 30
Split Flow Tol= 0.02
Split Flow Ratio= 0.02
Log Output Level= 0
Friction Slope Method= 1
Unsteady Friction Slope Method= 2
Unsteady Bridges Friction Slope Method= 1
Parabolic Critical Depth
Global Vel Dist=  1 , 1 , 1
Global Log Level= 0
CheckData=True
Encroach Param= -1, 0, 0, 0
BEGIN DESCRIPTION:
Multiple Run
END DESCRIPTION:

--- Plum Creek.f01 (steady flow) ---

Flow Title=Multiple
Number of Profiles=7
Profile Names=10-year,25-year,50-year,1pct_min,100-year,1pct_plu,500-year
River Rch & RM= Plum Creek,Reach-1,30209
     482     710     910     580    1157    2308    1896
River Rch & RM= Plum Creek,Reach-1,24469
     755    1131    1465     941    1878    3748    3130
River Rch & RM= Plum Creek,Reach-1,15079
     841    1261    1634    1050    2096    4181    3492
River Rch & RM= Plum Creek,Reach-1,10118
     941    1414    1836    1181    2357    4702    3937
River Rch & RM= Plum Creek,Reach-1,3919
    1008    1515    1966    1264    2522    5031    4206
Boundary for River Rch & Prof#=Plum Creek,Reach-1,1
Up Type=0
Dn Type=3
Dn Slope=0.005
Boundary for River Rch & Prof#=Plum Creek,Reach-1,2
Up Type=0
Dn Type=3
Dn Slope=0.005
Boundary for River Rch & Prof#=Plum Creek,Reach-1,3
Up Type=0
Dn Type=3
Dn Slope=0.005
Boundary for River Rch & Prof#=Plum Creek,Reach-1,4
Up Type=0
Dn Type=3
Dn Slope=0.005
Boundary for River Rch & Prof#=Plum Creek,Reach-1,5
Up Type=0
Dn Type=3
Dn Slope=0.005
Boundary for River Rch & Prof#=Plum Creek,Reach-1,6
Up Type=0
Dn Type=3
Dn Slope=0.005
Boundary for River Rch & Prof#=Plum Creek,Reach-1,7
Up Type=0
Dn Type=3
Dn Slope=0.005

--- Plum Creek.g01 (geometry) ---

Geom Title=Existing Conditions

River Reach=Plum Creek,Reach-1
Reach XY= 30
      1422055.00      6849488.00      1422035.38      6849808.47
      1421110.34      6850485.26      1420656.58      6851394.05
      1420635.60      6852208.12      1419106.57      6852491.43
      1418705.03      6852953.42      1419297.92      6854238.00
      1419054.74      6854718.05      1419404.14      6856027.69
      1419008.07      6856346.30      1418754.37      6857213.10
      1419297.67      6858237.90      1418312.32      6860038.10
      1419753.96      6861948.43      1419605.08      6863022.61
      1419953.03      6863632.35      1418954.25      6864527.31
      1419481.29      6865414.82      1420104.48      6865698.68
      1419604.46      6865862.87      1420151.87      6866240.18
      1419904.50      6866748.21      1420151.98      6867336.61
      1419405.38      6867703.16      1419458.51      6868129.52
      1419904.52      6868398.49      1419405.52      6868803.22
      1419508.40      6869686.79      1419755.00      6869688.00

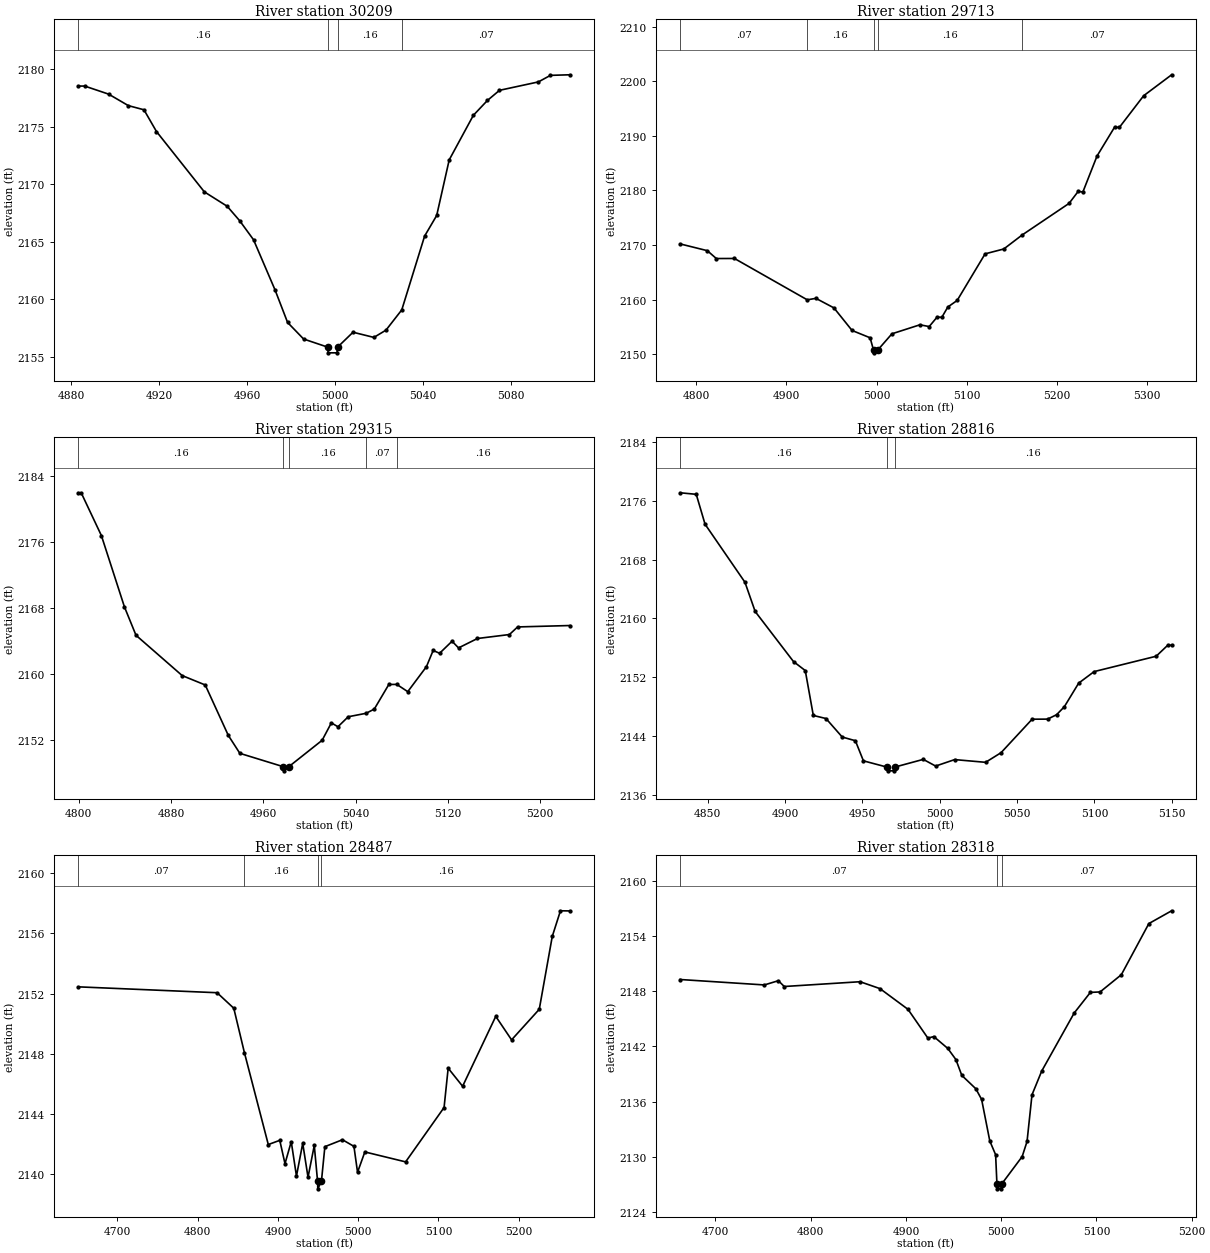
Type RM Length L Ch R = 1,30209,496,496,496
BEGIN DESCRIPTION:
Plum Creek 46.0
END DESCRIPTION:
XS GIS Cut Line= 3
      1421904.99      6849737.99      1421961.09      6849840.55
      1422005.01      6849938.01
#Sta/Elev= 30
  4883.1 2178.52  4886.0 2178.52  4896.9 2177.82  4905.9 2176.82  4913.0 2176.46
  4918.7 2174.57  4940.5 2169.33  4950.9 2168.08  4956.6 2166.82  4962.9 2165.17
  4972.7 2160.81  4978.4 2157.99  4985.7 2156.55  4996.6 2155.85  4996.9 2155.35
  5000.9 2155.35  5001.2 2155.85  5008.2 2157.14  5017.7 2156.69  5023.2 2157.32
  5030.4 2159.08  5040.8 2165.49  5046.3 2167.28  5052.0 2172.11  5063.0 2175.98
  5069.4 2177.27  5074.9 2178.15  5092.6 2178.88  5098.1 2179.45  5106.9 2179.50
#Mann=4,-1,0
  4883.1    0.16       0  4996.6    0.07       0  5001.2    0.16       0
  5030.4    0.07       0
Bank Sta=4996.6,5001.2
Exp/Cntr=0.3,0.1

Type RM Length L Ch R = 1,29713,398,398,398
BEGIN DESCRIPTION:
Plum Creek 45.0
END DESCRIPTION:
XS GIS Cut Line= 3
      1421605.00      6849937.97      1421588.49      6850155.04
      1421905.00      6850238.00
#Sta/Elev= 30
  4782.3 2170.20  4812.4 2168.96  4822.4 2167.52  4842.5 2167.53  4923.2 2159.95
  4932.8 2160.22  4952.8 2158.47  4972.9 2154.33  4992.9 2152.99  4996.7 2150.73
  4997.0 2150.23  5001.3 2150.73  5017.1 2153.72  5048.1 2155.37  5058.4 2155.05
  5067.2 2156.79  5072.4 2156.74  5079.1 2158.64  5089.4 2159.83  5120.4 2168.38
  5141.1 2169.27  5161.5 2171.84  5213.5 2177.63  5223.6 2179.83  5228.8 2179.72
  5244.5 2186.32  5264.0 2191.62  5269.2 2191.55  5296.2 2197.37  5327.2 2201.21
#Mann=5,-1,0
  4782.3    0.07       0  4923.2    0.16       0  4996.7    0.07       0
  5001.3    0.16       0  5161.5    0.07       0
Bank Sta=4996.7,5001.3
Exp/Cntr=0.3,0.1

Type RM Length L Ch R = 1,29315,499,499,499
BEGIN DESCRIPTION:
Plum Creek 44.0
END DESCRIPTION:
XS GIS Cut Line= 3
      1421105.03      6850338.00      1421305.27      6850333.05
      1421504.98      6850437.99
#Sta/Elev= 30
  4799.7 2181.93  4802.2 2181.93  4819.7 2176.75  4839.7 2168.10  4849.7 2164.67
  4889.7 2159.79  4909.7 2158.65  4929.7 2152.54  4939.7 2150.37  4977.4 2148.75
  4977.7 2148.25  4982.1 2148.75  5011.0 2151.95  5019.0 2154.06  5024.7 2153.59
  5033.6 2154.80  5049.1 2155.22  5056.2 2155.73  5068.8 2158.71  5075.7 2158.72
  5085.2 2157.84  5101.4 2160.87  5107.2 2162.83  5112.8 2162.49  5123.6 2163.95
  5129.2 2163.14  5145.6 2164.28  5173.3 2164.76  5180.4 2165.68  5225.6 2165.85
#Mann=5,-1,0
  4799.7    0.16       0  4977.4    0.07       0  4982.1    0.16       0
  5049.1    0.07       0  5075.7    0.16       0
Bank Sta=4977.4,4982.1
Exp/Cntr=0.3,0.1

Type RM Length L Ch R = 1,28816,329,329,329
BEGIN DESCRIPTION:
Plum Creek 43.0
END DESCRIPTION:
XS GIS Cut Line= 3
      1421055.01      6850538.04      1421105.45      6850698.19
      1421255.00      6850688.00
#Sta/Elev= 30
  4832.1 2177.11  4842.5 2176.90  4848.2 2172.83  4874.0 2164.93  4880.6 2160.95
  4905.4 2154.13  4913.0 2152.91  4918.2 2146.80  4926.4 2146.38  4936.9 2143.86
  4945.4 2143.36  4950.6 2140.62  4966.0 2139.76  4966.4 2139.26  4970.4 2139.26
  4970.7 2139.76  4989.3 2140.82  4997.3 2139.91  5009.6 2140.79  5029.6 2140.42
  5039.6 2141.73  5059.7 2146.29  5069.7 2146.30  5075.5 2146.90  5080.5 2147.98
  5089.8 2151.20  5099.8 2152.77  5139.9 2154.86  5147.4 2156.36  5149.9 2156.36
#Mann=3,-1,0
  4832.1    0.16       0  4966.0    0.07       0  4970.7    0.16       0
Bank Sta=4966,4970.7
Exp/Cntr=0.3,0.1

Type RM Length L Ch R = 1,28487,169,169,169
BEGIN DESCRIPTION:
Plum Creek 4178
END DESCRIPTION:
XS GIS Cut Line= 3
      1420729.09      6850770.66      1420996.84      6850994.05
      1421256.45      6851039.77
#Sta/Elev= 30
  4651.3 2152.45  4824.2 2152.06  4845.0 2151.03  4858.3 2148.07  4888.0 2141.98
  4902.3 2142.26  4908.8 2140.71  4916.6 2142.17  4923.1 2139.89  4930.9 2142.06
  4937.5 2139.81  4945.3 2141.92  4949.4 2139.54  4949.7 2139.04  4954.2 2139.54
  4958.5 2141.84  4980.4 2142.30  4994.7 2141.86  4999.2 2140.14  5008.3 2141.49
  5059.1 2140.83  5107.0 2144.44  5112.1 2147.05  5130.1 2145.85  5171.4 2150.49
  5191.1 2148.93  5225.6 2150.96  5241.8 2155.80  5252.0 2157.50  5263.6 2157.49
#Mann=4,-1,0
  4651.3    0.07       0  4858.3    0.16       0  4949.4    0.07       0
  4954.2    0.16       0
Bank Sta=4949.4,4954.2
Exp/Cntr=0.3,0.1

Type RM Length L Ch R = 1,28318,497,497,497
BEGIN DESCRIPTION:
Plum Creek 42.0
END DESCRIPTION:
XS GIS Cut Line= 3
      1420630.27      6850929.85      1420903.45      6851127.36
      1421078.41      6851164.70
#Sta/Elev= 30
  4662.9 2149.28  4751.3 2148.69  4766.0 2149.15  4772.2 2148.52  4851.8 2149.04
  4872.7 2148.29  4902.1 2146.04  4923.0 2142.91  4929.2 2143.08  4943.9 2141.79
  4952.4 2140.58  4958.6 2138.86  4973.3 2137.41  4979.4 2136.25  4988.0 2131.73
  4994.1 2130.24  4995.5 2127.03  4995.8 2126.53  4999.9 2126.53  5000.3 2127.03
  5022.0 2130.04  5027.1 2131.68  5032.3 2136.75  5042.5 2139.33  5076.6 2145.64
  5093.6 2147.88  5103.8 2147.93  5126.1 2149.80  5155.0 2155.36  5178.9 2156.75
#Mann=3,-1,0
  4662.9    0.07       0  4995.5    0.07       0  5000.3    0.07       0
Bank Sta=4995.5,5000.3
Exp/Cntr=0.3,0.1

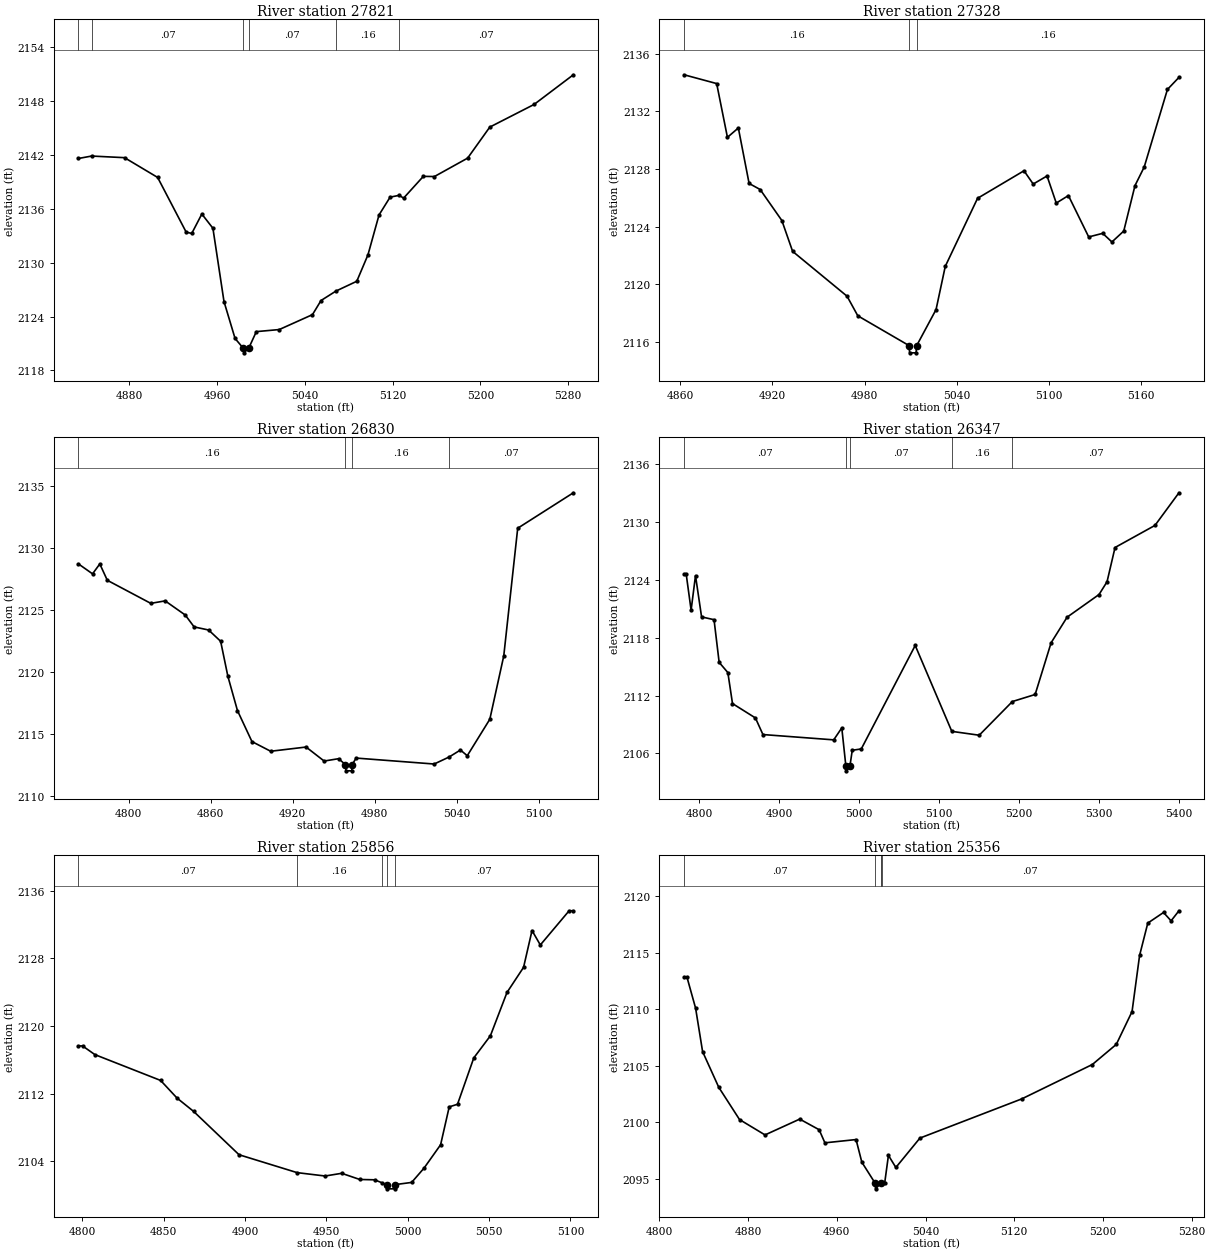
Type RM Length L Ch R = 1,27821,493,493,493
BEGIN DESCRIPTION:
Plum Creek 41.0
END DESCRIPTION:
XS GIS Cut Line= 3
      1420553.30      6851480.91      1420718.55      6851501.23
      1421000.41      6851460.42
#Sta/Elev= 30
  4833.5 2141.58  4845.5 2141.85  4875.5 2141.67  4905.7 2139.47  4931.7 2133.39
  4936.8 2133.24  4946.0 2135.40  4956.1 2133.82  4966.2 2125.67  4976.3 2121.56
  4983.9 2120.46  4984.3 2119.96  4988.7 2120.46  4995.7 2122.32  5016.6 2122.55
  5046.9 2124.21  5054.7 2125.78  5068.3 2126.83  5087.3 2127.92  5097.5 2130.86
  5107.6 2135.30  5117.7 2137.28  5126.0 2137.48  5130.0 2137.17  5148.0 2139.59
  5158.1 2139.57  5188.4 2141.62  5208.6 2145.07  5249.0 2147.59  5284.8 2150.89
#Mann=6,-1,0
  4833.5    0.16       0  4845.5    0.07       0  4983.9    0.07       0
  4988.7    0.07       0  5068.3    0.16       0  5126.0    0.07       0
Bank Sta=4983.9,4988.7
Exp/Cntr=0.3,0.1

Type RM Length L Ch R = 1,27328,498,498,498
BEGIN DESCRIPTION:
Plum Creek 40.0
END DESCRIPTION:
XS GIS Cut Line= 3
      1420555.03      6851788.03      1420651.01      6851886.35
      1420804.99      6851987.99
#Sta/Elev= 30
  4862.6 2134.53  4883.8 2133.92  4890.8 2130.19  4897.9 2130.84  4904.9 2126.99
  4912.1 2126.57  4926.2 2124.42  4933.2 2122.28  4968.6 2119.17  4975.6 2117.81
  5009.0 2115.74  5009.3 2115.24  5013.5 2115.24  5013.9 2115.74  5026.5 2118.24
  5032.5 2121.24  5053.5 2125.96  5083.7 2127.87  5089.7 2126.95  5098.7 2127.51
  5104.7 2125.63  5112.6 2126.15  5125.8 2123.28  5134.9 2123.53  5140.9 2122.93
  5148.6 2123.69  5155.9 2126.84  5161.9 2128.13  5177.0 2133.51  5184.5 2134.35
#Mann=3,-1,0
  4862.6    0.16       0  5009.0    0.07       0  5013.9    0.16       0
Bank Sta=5009,5013.9
Exp/Cntr=0.3,0.1

Type RM Length L Ch R = 1,26830,483,483,483
BEGIN DESCRIPTION:
Plum Creek 39.0
END DESCRIPTION:
XS GIS Cut Line= 3
      1420505.00      6852038.01      1420581.95      6852261.86
      1420704.96      6852238.01
#Sta/Elev= 30
  4763.3 2128.70  4773.6 2127.90  4778.9 2128.70  4784.4 2127.38  4816.2 2125.52
  4826.7 2125.72  4841.4 2124.58  4847.9 2123.62  4858.5 2123.37  4867.3 2122.46
  4872.6 2119.63  4879.6 2116.87  4890.2 2114.37  4903.9 2113.59  4929.8 2113.93
  4943.0 2112.80  4953.6 2112.99  4958.6 2112.51  4959.0 2112.01  4963.2 2112.01
  4963.5 2112.51  4966.4 2113.04  5023.5 2112.56  5034.5 2113.13  5042.7 2113.69
  5047.7 2113.23  5064.2 2116.17  5074.4 2121.28  5084.6 2131.58  5125.3 2134.44
#Mann=4,-1,0
  4763.3    0.16       0  4958.6    0.07       0  4963.5    0.16       0
  5034.5    0.07       0
Bank Sta=4958.6,4963.5
Exp/Cntr=0.3,0.1

Type RM Length L Ch R = 1,26347,491,491,491
BEGIN DESCRIPTION:
Plum Creek 38.0
END DESCRIPTION:
XS GIS Cut Line= 3
      1420055.00      6852188.00      1420144.95      6852387.89
      1420155.00      6852787.96
#Sta/Elev= 30
  4780.8 2124.56  4783.5 2124.56  4789.6 2120.85  4795.1 2124.43  4802.7 2120.15
  4818.3 2119.86  4824.7 2115.44  4835.6 2114.38  4841.4 2111.17  4870.1 2109.68
  4879.5 2107.96  4968.1 2107.41  4978.2 2108.65  4983.3 2104.70  4983.7 2104.20
  4988.4 2104.70  4991.3 2106.33  5002.6 2106.47  5070.1 2117.19  5115.9 2108.29
  5150.2 2107.89  5191.7 2111.38  5220.2 2112.11  5240.2 2117.47  5260.2 2120.12
  5300.2 2122.47  5310.2 2123.79  5320.2 2127.34  5370.2 2129.63  5400.2 2133.01
#Mann=5,-1,0
  4780.8    0.07       0  4983.3    0.07       0  4988.4    0.07       0
  5115.9    0.16       0  5191.7    0.07       0
Bank Sta=4983.3,4988.4
Exp/Cntr=0.3,0.1

Type RM Length L Ch R = 1,25856,500,500,500
BEGIN DESCRIPTION:
Plum Creek 37.0
END DESCRIPTION:
XS GIS Cut Line= 3
      1419705.00      6852338.03      1419734.95      6852538.20
      1419755.00      6852638.01
#Sta/Elev= 30
  4797.6 2117.64  4800.1 2117.64  4807.7 2116.61  4848.1 2113.55  4858.2 2111.46
  4868.4 2109.88  4896.3 2104.75  4932.0 2102.63  4949.2 2102.23  4959.4 2102.55
  4970.5 2101.82  4979.6 2101.78  4983.9 2101.45  4987.1 2101.21  4987.5 2100.71
  4991.9 2100.71  4992.2 2101.21  5002.4 2101.47  5010.0 2103.16  5020.2 2105.93
  5025.5 2110.42  5030.6 2110.73  5040.6 2116.22  5050.8 2118.84  5061.0 2123.97
  5071.2 2126.95  5076.4 2131.31  5081.5 2129.60  5099.2 2133.65  5101.8 2133.65
#Mann=5,-1,0
  4797.6    0.07       0  4932.0    0.16       0  4983.9    0.07       0
  4987.1    0.07       0  4992.2    0.07       0
Bank Sta=4987.1,4992.2
Exp/Cntr=0.3,0.1

Type RM Length L Ch R = 1,25356,493,493,493
BEGIN DESCRIPTION:
Plum Creek 36.0
END DESCRIPTION:
XS GIS Cut Line= 3
      1419305.00      6852387.99      1419355.35      6852558.51
      1419555.02      6852738.02
#Sta/Elev= 30
  4822.2 2112.83  4824.8 2112.83  4832.6 2110.08  4838.9 2106.24  4853.5 2103.08
  4872.2 2100.23  4895.2 2098.87  4926.5 2100.27  4944.0 2099.33  4949.2 2098.17
  4977.3 2098.46  4982.5 2096.46  4994.5 2094.60  4994.9 2094.10  4999.7 2094.60
  5000.0 2094.60  5000.4 2094.60  5003.1 2094.60  5006.5 2097.06  5013.2 2095.99
  5034.9 2098.59  5126.8 2102.06  5190.4 2105.10  5212.0 2106.88  5226.2 2109.78
  5233.0 2114.75  5240.4 2117.61  5254.6 2118.55  5261.4 2117.81  5268.5 2118.70
#Mann=5,-1,0
  4822.2    0.07       0  4994.5    0.07       0  4999.7    0.07       0
  5000.0    0.16       0  5000.4    0.07       0
Bank Sta=4994.5,4999.7
Exp/Cntr=0.3,0.1

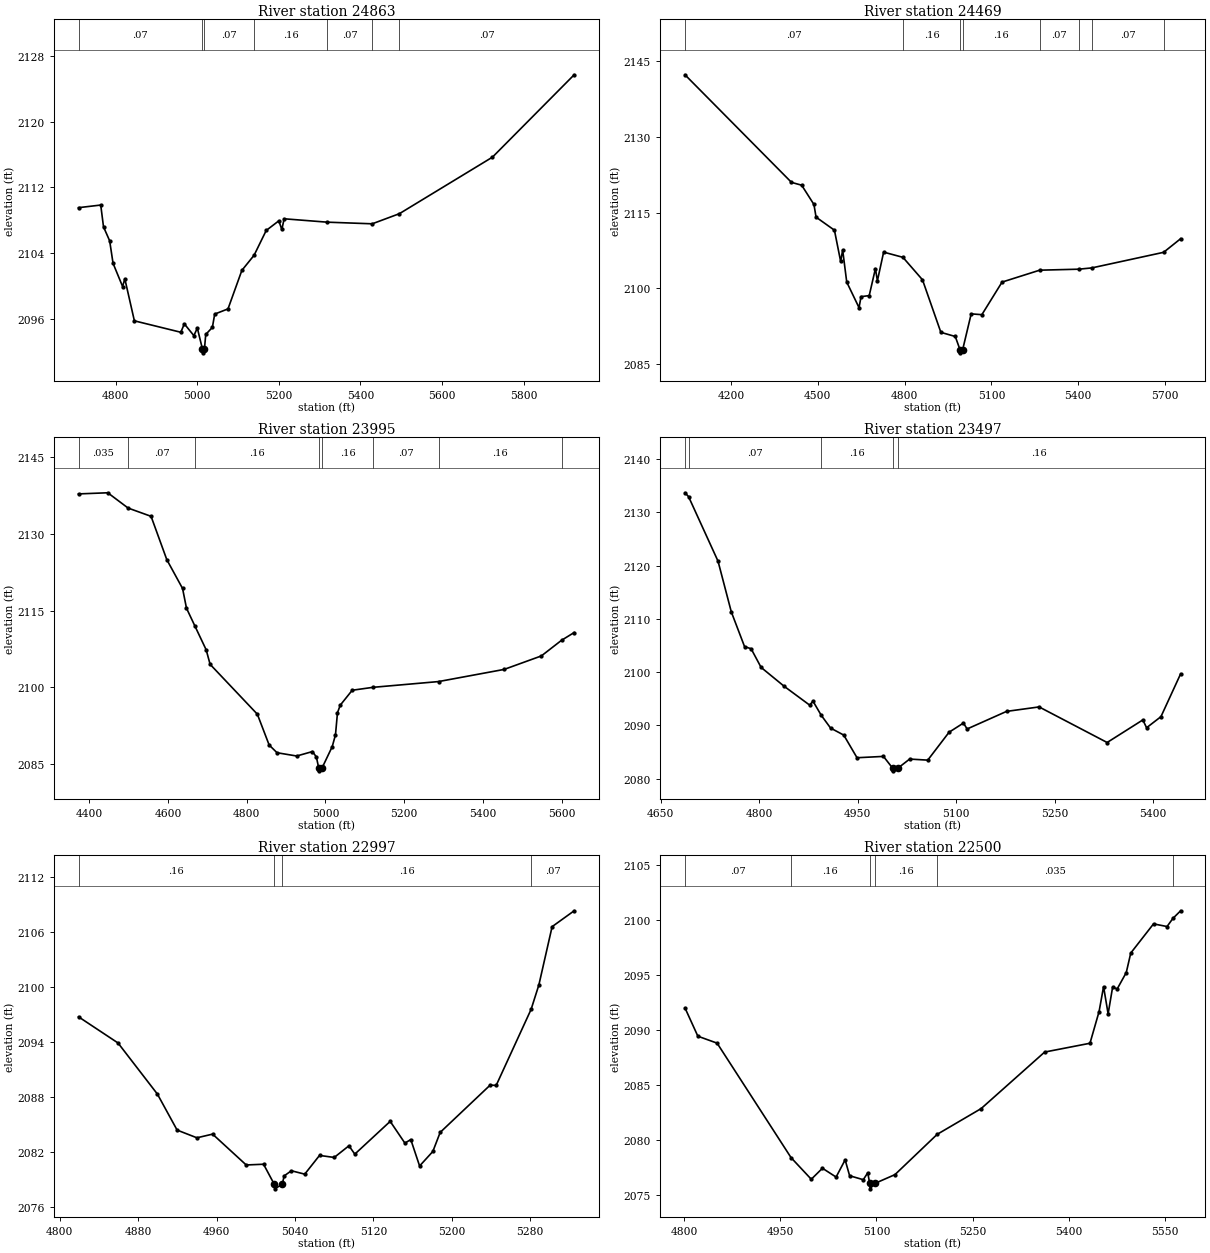
Type RM Length L Ch R = 1,24863,394,394,394
BEGIN DESCRIPTION:
Plum Creek 35.0
END DESCRIPTION:
XS GIS Cut Line= 3
      1419105.00      6852338.00      1418988.51      6852605.10
      1419804.96      6853037.98
#Sta/Elev= 30
  4708.6 2109.53  4763.1 2109.85  4769.9 2107.20  4785.0 2105.50  4793.3 2102.77
  4816.7 2099.95  4822.2 2100.88  4845.6 2095.78  4959.5 2094.39  4968.1 2095.41
  4991.5 2093.98  5000.0 2094.90  5012.3 2092.39  5012.7 2091.89  5017.5 2092.39
  5020.6 2094.12  5036.9 2094.99  5042.6 2096.60  5075.2 2097.23  5109.2 2101.91
  5139.2 2103.75  5168.9 2106.76  5199.8 2107.93  5207.2 2106.88  5212.9 2108.18
  5318.1 2107.77  5428.9 2107.57  5495.5 2108.80  5723.7 2115.67  5924.1 2125.68
#Mann=7,-1,0
  4708.6    0.07       0  5012.3    0.07       0  5017.5    0.07       0
  5139.2    0.16       0  5318.1    0.07       0  5428.9    0.16       0
  5495.5    0.07       0
Bank Sta=5012.3,5017.5
Exp/Cntr=0.3,0.1

Type RM Length L Ch R = 1,24469,474,474,474
BEGIN DESCRIPTION:
Plum Creek 34.0
END DESCRIPTION:
XS GIS Cut Line= 3
      1418097.56      6852155.15      1418755.14      6852853.06
      1419501.19      6852962.30
#Sta/Elev= 30
  4041.1 2142.22  4409.2 2120.96  4444.4 2120.40  4486.8 2116.59  4494.1 2114.09
  4557.6 2111.51  4579.1 2105.34  4586.0 2107.60  4600.1 2101.26  4642.6 2096.21
  4649.6 2098.38  4677.8 2098.59  4699.2 2103.92  4706.1 2101.51  4727.6 2107.18
  4794.3 2106.15  4861.9 2101.71  4925.4 2091.33  4975.2 2090.51  4992.3 2087.78
  4992.8 2087.28  5000.2 2087.78  5030.2 2094.98  5067.1 2094.82  5136.9 2101.26
  5266.8 2103.61  5402.5 2103.81  5447.0 2104.06  5695.1 2107.14  5754.0 2109.83
#Mann=8,-1,0
  4041.1    0.07       0  4794.3    0.16       0  4992.3    0.07       0
  5000.2    0.16       0  5266.8    0.07       0  5402.5    0.16       0
  5447.0    0.07       0  5695.1    0.16       0
Bank Sta=4992.3,5000.2
Exp/Cntr=0.3,0.1

Type RM Length L Ch R = 1,23995,498,498,498
BEGIN DESCRIPTION:
Plum Creek 33.0
END DESCRIPTION:
XS GIS Cut Line= 3
      1418320.73      6853190.30      1418947.92      6853187.98
      1419570.22      6853078.22
#Sta/Elev= 30
  4372.8 2137.73  4447.1 2137.95  4498.8 2134.97  4557.1 2133.36  4597.1 2124.91
  4637.1 2119.30  4647.1 2115.45  4669.0 2111.89  4697.1 2107.34  4707.1 2104.51
  4827.1 2094.79  4857.1 2088.78  4877.1 2087.28  4927.1 2086.64  4967.1 2087.51
  4977.1 2086.44  4983.1 2084.25  4983.6 2083.75  4991.1 2084.25  5017.3 2088.47
  5025.6 2090.78  5030.6 2095.07  5037.7 2096.55  5068.1 2099.46  5121.1 2100.03
  5287.3 2101.15  5454.0 2103.52  5548.6 2106.15  5599.9 2109.20  5631.9 2110.71
#Mann=8,-1,0
  4372.8   0.035       0  4498.8    0.07       0  4669.0    0.16       0
  4983.1    0.07       0  4991.1    0.16       0  5121.1    0.07       0
  5287.3    0.16       0  5599.9    0.07       0
Bank Sta=4983.1,4991.1
Exp/Cntr=0.3,0.1

Type RM Length L Ch R = 1,23497,500,500,500
BEGIN DESCRIPTION:
Plum Creek 32.0
END DESCRIPTION:
XS GIS Cut Line= 3
      1418605.00      6853538.00      1418915.57      6853578.46
      1419304.98      6853787.99
#Sta/Elev= 30
  4686.8 2133.67  4692.2 2132.96  4737.2 2120.82  4757.4 2111.31  4777.6 2104.79
  4787.6 2104.39  4802.8 2100.89  4838.1 2097.33  4876.8 2093.81  4881.9 2094.55
  4894.4 2091.91  4908.7 2089.50  4928.8 2088.18  4949.0 2083.93  4989.3 2084.18
  5003.3 2081.97  5003.8 2081.47  5011.3 2081.97  5029.2 2083.68  5056.8 2083.48
  5089.3 2088.72  5111.2 2090.44  5116.8 2089.33  5176.9 2092.63  5226.5 2093.47
  5330.2 2086.79  5384.6 2091.03  5390.3 2089.56  5412.2 2091.64  5442.2 2099.68
#Mann=5,-1,0
  4686.8   0.035       0  4692.2    0.07       0  4894.4    0.16       0
  5003.3    0.07       0  5011.3    0.16       0
Bank Sta=5003.3,5011.3
Exp/Cntr=0.3,0.1

Type RM Length L Ch R = 1,22997,497,497,497
BEGIN DESCRIPTION:
Plum Creek 31.0
END DESCRIPTION:
XS GIS Cut Line= 3
      1418904.97      6854038.00      1419084.69      6854018.30
      1419354.98      6853838.01
#Sta/Elev= 30
  4819.2 2096.73  4859.5 2093.88  4899.7 2088.31  4919.8 2084.39  4940.0 2083.55
  4956.0 2083.95  4990.3 2080.59  5008.0 2080.67  5018.9 2078.49  5019.4 2077.99
  5027.1 2078.49  5029.0 2079.40  5036.4 2079.96  5050.0 2079.59  5065.1 2081.63
  5080.1 2081.41  5095.1 2082.68  5101.1 2081.77  5137.2 2085.34  5152.2 2082.97
  5158.2 2083.36  5167.2 2080.48  5180.7 2082.06  5188.2 2084.14  5239.3 2089.30
  5245.3 2089.25  5281.0 2097.55  5288.9 2100.21  5302.4 2106.55  5324.9 2108.28
#Mann=4,-1,0
  4819.2    0.16       0  5018.9    0.07       0  5027.1    0.16       0
  5281.0    0.07       0
Bank Sta=5018.9,5027.1
Exp/Cntr=0.3,0.1

Type RM Length L Ch R = 1,22500,495,495,495
BEGIN DESCRIPTION:
Plum Creek 30.0
END DESCRIPTION:
XS GIS Cut Line= 3
      1419004.98      6854388.00      1419203.29      6854377.29
      1419605.00      6854788.00
#Sta/Elev= 30
  4801.4 2092.03  4821.5 2089.46  4851.5 2088.83  4966.9 2078.43  4998.4 2076.47
  5015.8 2077.47  5037.1 2076.67  5051.2 2078.23  5058.2 2076.79  5079.5 2076.43
  5086.5 2077.06  5089.5 2076.10  5090.0 2075.60  5097.9 2076.10  5128.9 2076.89
  5194.8 2080.55  5263.4 2082.89  5362.4 2088.02  5433.1 2088.82  5447.3 2091.70
  5454.3 2093.96  5461.4 2091.49  5468.4 2093.91  5475.6 2093.76  5489.7 2095.24
  5496.7 2097.01  5532.2 2099.66  5553.3 2099.42  5562.5 2100.16  5574.5 2100.85
#Mann=6,-1,0
  4801.4    0.07       0  4966.9    0.16       0  5089.5    0.07       0
  5097.9    0.16       0  5194.8   0.035       0  5562.5    0.07       0
Bank Sta=5089.5,5097.9
Exp/Cntr=0.3,0.1

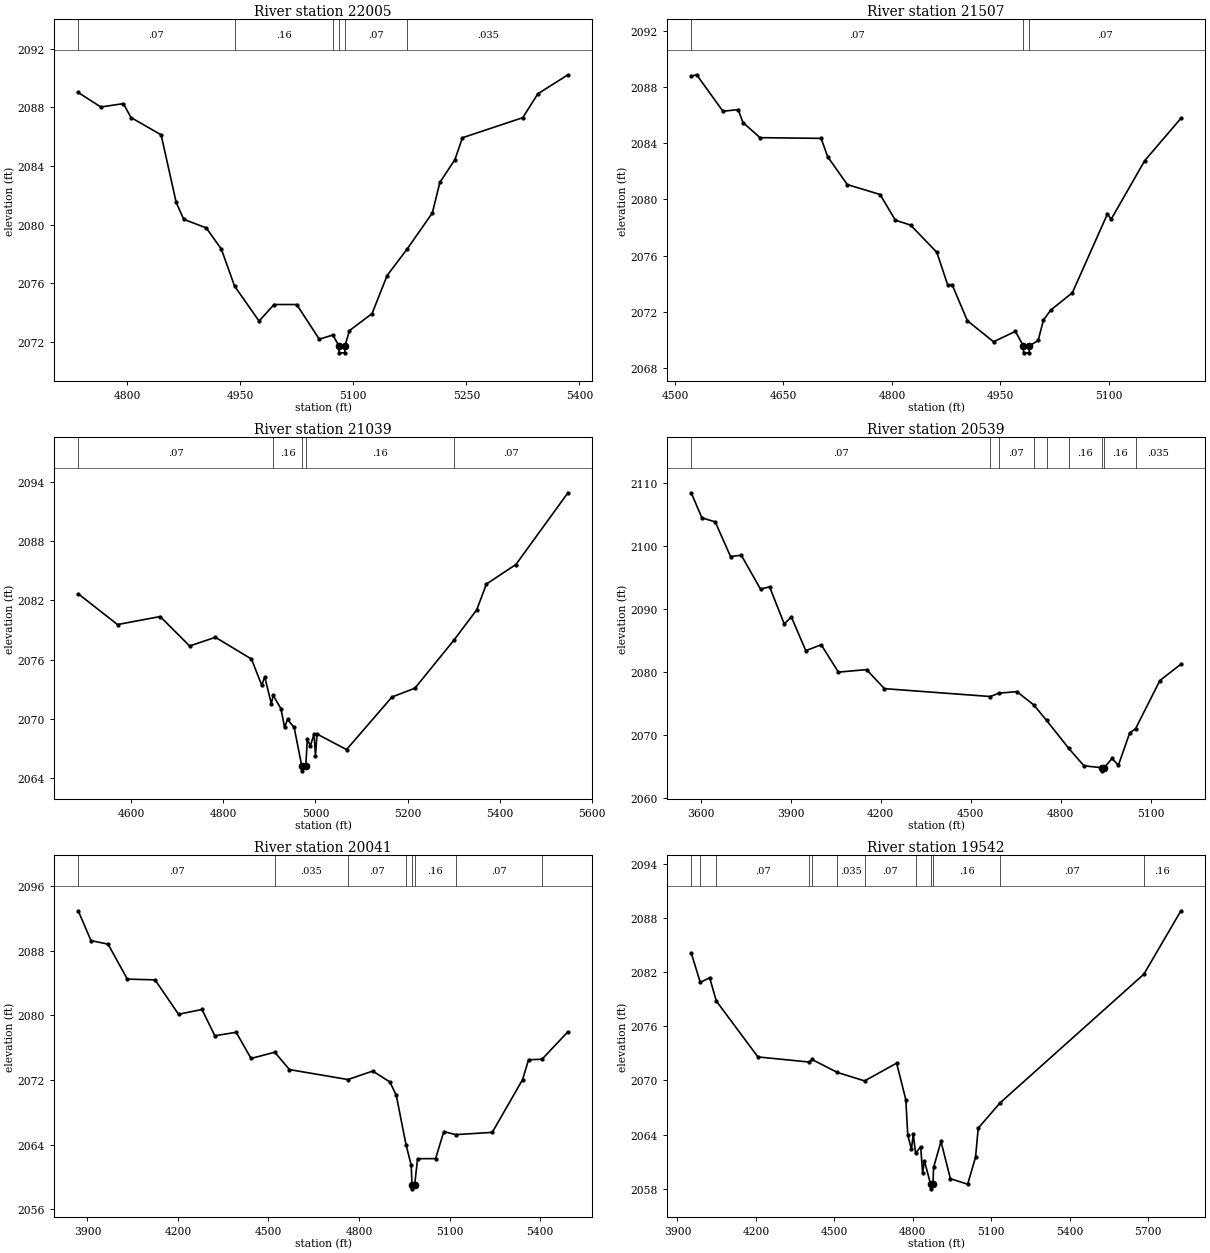
Type RM Length L Ch R = 1,22005,498,498,498
BEGIN DESCRIPTION:
Plum Creek 29.0
END DESCRIPTION:
XS GIS Cut Line= 3
      1418855.02      6854788.00      1419120.22      6854787.18
      1419505.02      6854788.00
#Sta/Elev= 30
  4734.8 2089.02  4764.8 2088.03  4794.8 2088.26  4804.8 2087.31  4844.8 2086.13
  4864.8 2081.52  4874.8 2080.36  4904.8 2079.77  4924.8 2078.32  4942.3 2075.80
  4974.8 2073.41  4994.8 2074.54  5024.8 2074.54  5054.8 2072.17  5072.8 2072.46
  5080.5 2071.74  5081.0 2071.24  5088.5 2071.24  5089.0 2071.74  5094.8 2072.76
  5124.8 2073.92  5144.8 2076.52  5171.8 2078.36  5204.8 2080.79  5214.8 2082.88
  5234.8 2084.44  5244.8 2085.93  5324.8 2087.30  5344.8 2088.93  5384.8 2090.23
#Mann=6,-1,0
  4734.8    0.07       0  4942.3    0.16       0  5072.8    0.07       0
  5080.5    0.07       0  5089.0    0.07       0  5171.8   0.035       0
Bank Sta=5080.5,5089
Exp/Cntr=0.3,0.1

Type RM Length L Ch R = 1,21507,468,468,468
BEGIN DESCRIPTION:
Plum Creek 28.0
END DESCRIPTION:
XS GIS Cut Line= 3
      1418804.96      6854937.97      1419205.45      6855198.19
      1419404.99      6855188.00
#Sta/Elev= 30
  4522.4 2088.78  4530.0 2088.88  4566.3 2086.28  4587.4 2086.40  4594.0 2085.48
  4617.6 2084.40  4702.1 2084.35  4711.2 2083.04  4738.3 2081.06  4783.7 2080.35
  4804.8 2078.52  4825.9 2078.17  4862.2 2076.23  4877.3 2073.89  4883.3 2073.93
  4904.4 2071.36  4940.6 2069.86  4970.9 2070.60  4981.7 2069.57  4982.2 2069.07
  4989.8 2069.07  4990.3 2069.57  5002.3 2069.95  5009.6 2071.40  5019.6 2072.11
  5049.6 2073.35  5098.2 2078.97  5103.2 2078.58  5149.7 2082.76  5199.8 2085.78
#Mann=3,-1,0
  4522.4    0.07       0  4981.7    0.07       0  4990.3    0.07       0
Bank Sta=4981.7,4990.3
Exp/Cntr=0.3,0.1

Type RM Length L Ch R = 1,21039,500,500,500
BEGIN DESCRIPTION:
Plum Creek 27.0
END DESCRIPTION:
XS GIS Cut Line= 3
      1418755.03      6855288.02      1419154.91      6855613.04
      1419555.01      6855237.99
#Sta/Elev= 30
  4484.7 2082.65  4570.1 2079.54  4662.8 2080.35  4726.7 2077.37  4782.7 2078.25
  4861.0 2076.05  4883.3 2073.40  4889.8 2074.25  4904.1 2071.54  4908.2 2072.37
  4925.0 2071.03  4932.9 2069.13  4939.3 2069.94  4953.7 2069.13  4970.2 2065.24
  4970.7 2064.74  4978.9 2065.24  4982.4 2067.93  4988.9 2067.26  4996.8 2068.46
  5000.0 2066.29  5003.5 2068.46  5067.5 2066.89  5166.2 2072.21  5216.0 2073.10
  5300.7 2077.96  5350.3 2081.03  5371.3 2083.64  5435.3 2085.61  5548.4 2092.87
#Mann=5,-1,0
  4484.7    0.07       0  4908.2    0.16       0  4970.2    0.07       0
  4978.9    0.16       0  5300.7    0.07       0
Bank Sta=4970.2,4978.9
Exp/Cntr=0.3,0.1

Type RM Length L Ch R = 1,20539,498,498,498
BEGIN DESCRIPTION:
Plum Creek 26.0
END DESCRIPTION:
XS GIS Cut Line= 3
      1418204.98      6855237.99      1419405.27      6856018.06
      1419604.97      6856038.00
#Sta/Elev= 30
  3568.5 2108.47  3604.3 2104.48  3648.6 2103.84  3699.7 2098.33  3735.5 2098.54
  3799.5 2093.15  3829.8 2093.51  3878.6 2087.61  3902.3 2088.73  3950.4 2083.36
  4001.8 2084.30  4059.1 2079.95  4152.9 2080.35  4212.5 2077.32  4565.4 2076.07
  4594.3 2076.60  4653.8 2076.85  4710.3 2074.73  4753.1 2072.26  4826.2 2067.86
  4877.5 2065.05  4936.4 2064.75  4936.9 2064.25  4945.3 2064.75  4971.1 2066.22
  4992.2 2065.13  5029.9 2070.27  5049.6 2070.96  5130.4 2078.60  5200.7 2081.22
#Mann=9,-1,0
  3568.5    0.07       0  4565.4   0.035       0  4594.3    0.07       0
  4710.3   0.035       0  4753.1    0.07       0  4826.2    0.16       0
  4936.4    0.07       0  4945.3    0.16       0  5049.6   0.035       0
Bank Sta=4936.4,4945.3
Exp/Cntr=0.3,0.1

Type RM Length L Ch R = 1,20041,499,499,499
BEGIN DESCRIPTION:
Plum Creek 25.0
END DESCRIPTION:
XS GIS Cut Line= 3
      1418255.00      6855538.00      1419064.39      6856327.10
      1419555.04      6856288.00
#Sta/Elev= 30
  3869.6 2092.95  3911.9 2089.26  3968.5 2088.82  4032.3 2084.49  4124.1 2084.40
  4202.0 2080.14  4279.7 2080.73  4322.2 2077.48  4392.9 2077.91  4442.3 2074.67
  4520.8 2075.44  4569.6 2073.29  4763.2 2072.06  4845.6 2073.11  4902.1 2071.76
  4923.3 2070.12  4956.0 2063.94  4972.9 2061.46  4975.4 2059.03  4975.9 2058.53
  4984.3 2059.03  4994.0 2062.26  5053.7 2062.27  5080.9 2065.62  5120.2 2065.24
  5241.4 2065.52  5341.7 2072.04  5361.7 2074.51  5406.2 2074.57  5492.2 2077.98
#Mann=8,-1,0
  3869.6    0.07       0  4520.8   0.035       0  4763.2    0.07       0
  4956.0    0.16       0  4975.4    0.07       0  4984.3    0.16       0
  5120.2    0.07       0  5406.2    0.16       0
Bank Sta=4975.4,4984.3
Exp/Cntr=0.3,0.1

Type RM Length L Ch R = 1,19542,499,499,499
BEGIN DESCRIPTION:
Plum Creek 24.0
END DESCRIPTION:
XS GIS Cut Line= 3
      1418354.97      6855987.97      1419134.88      6856687.41
      1419955.03      6856788.00
#Sta/Elev= 30
  3952.4 2084.16  3987.2 2080.88  4023.1 2081.40  4048.4 2078.82  4207.7 2072.61
  4404.4 2072.04  4414.4 2072.33  4511.6 2070.89  4616.0 2069.95  4738.5 2071.92
  4773.6 2067.87  4781.1 2063.93  4795.3 2062.36  4802.0 2064.09  4810.9 2061.92
  4830.5 2062.64  4837.9 2059.74  4844.7 2061.08  4868.6 2058.47  4869.1 2057.97
  4877.6 2058.47  4879.8 2060.34  4908.2 2063.23  4944.1 2059.10  5010.2 2058.48
  5040.4 2061.48  5050.7 2064.71  5134.6 2067.52  5684.7 2081.80  5826.3 2088.83
#Mann=12,-1,0
  3952.4    0.07       0  3987.2   0.035       0  4048.4    0.07       0
  4404.4   0.035       0  4414.4    0.07       0  4511.6   0.035       0
  4616.0    0.07       0  4810.9    0.16       0  4868.6    0.07       0
  4877.6    0.16       0  5134.6    0.07       0  5684.7    0.16       0
Bank Sta=4868.6,4877.6
Exp/Cntr=0.3,0.1

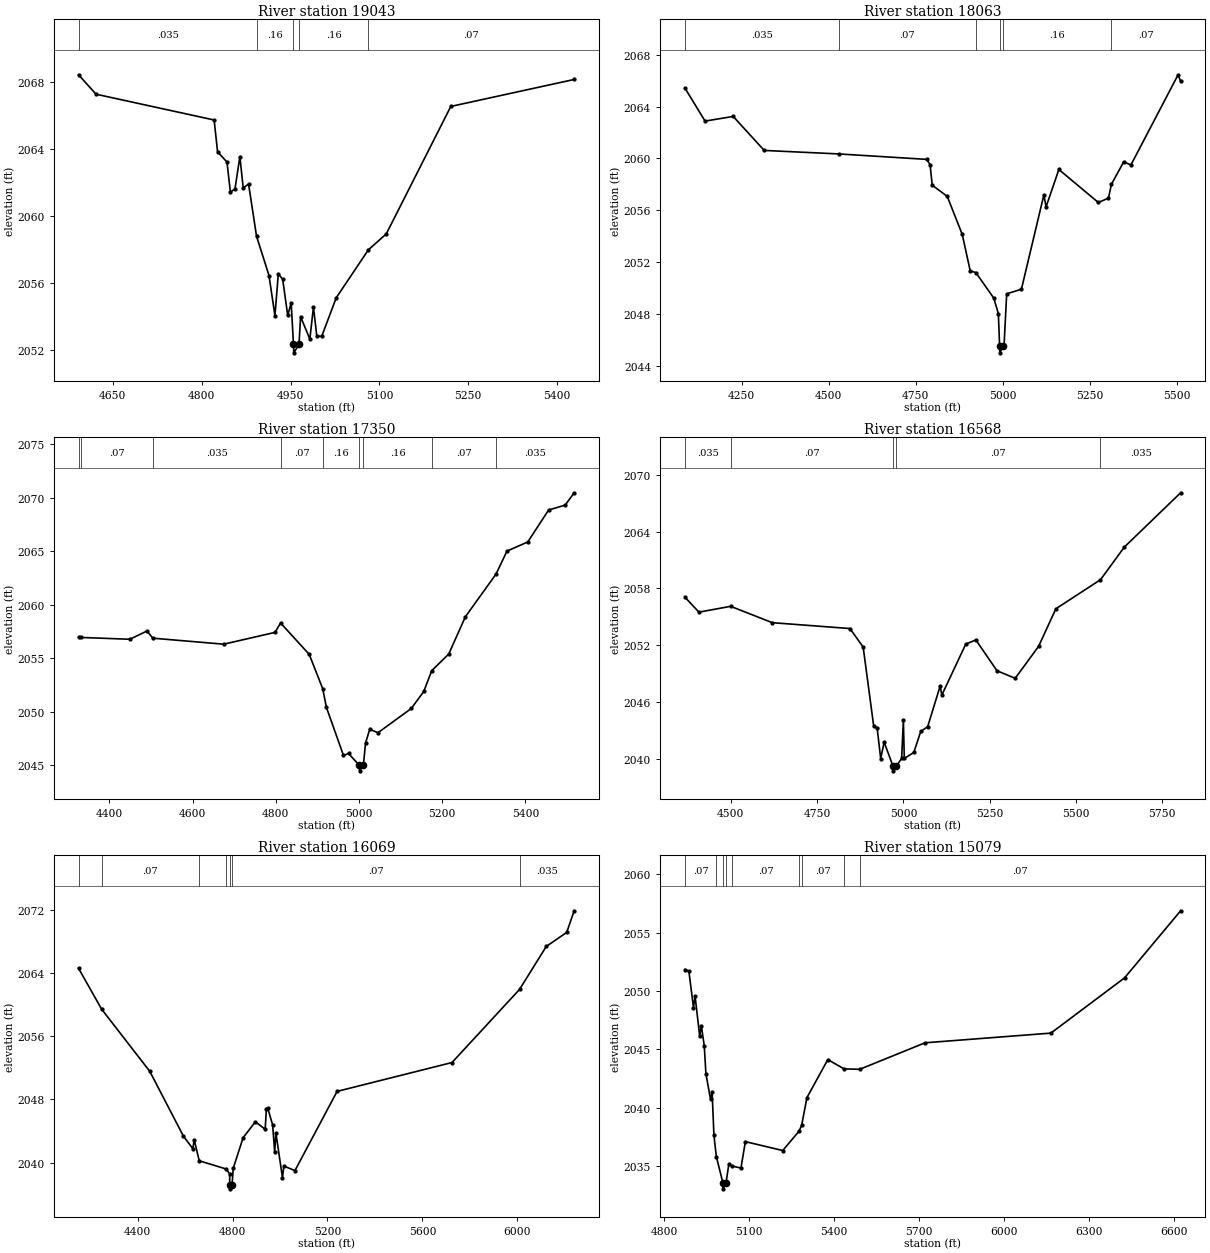
Type RM Length L Ch R = 1,19043,980,980,980
BEGIN DESCRIPTION:
Plum Creek 23.0
END DESCRIPTION:
XS GIS Cut Line= 3
      1418655.01      6856688.01      1418855.41      6857043.17
      1419255.04      6856887.98
#Sta/Elev= 30
  4592.2 2068.46  4621.8 2067.30  4821.1 2065.76  4826.9 2063.86  4842.8 2063.25
  4848.5 2061.45  4856.3 2061.65  4864.5 2063.57  4870.2 2061.70  4879.2 2061.94
  4892.6 2058.83  4913.7 2056.47  4923.7 2054.08  4929.4 2056.57  4936.7 2056.26
  4945.3 2054.09  4951.1 2054.84  4955.0 2052.36  4955.5 2051.86  4964.3 2052.36
  4967.0 2054.02  4982.6 2052.68  4988.7 2054.59  4994.4 2052.85  5002.7 2052.85
  5027.2 2055.15  5081.4 2058.01  5111.6 2058.96  5220.5 2066.57  5428.7 2068.18
#Mann=5,-1,0
  4592.2   0.035       0  4892.6    0.16       0  4955.0    0.07       0
  4964.3    0.16       0  5081.4    0.07       0
Bank Sta=4955,4964.3
Exp/Cntr=0.3,0.1

Type RM Length L Ch R = 1,18063,713,713,713
BEGIN DESCRIPTION:
Plum Creek 22.0
END DESCRIPTION:
XS GIS Cut Line= 3
      1418205.02      6857288.01      1418996.19      6857744.07
      1419405.01      6857438.00
#Sta/Elev= 30
  4086.8 2065.42  4144.5 2062.88  4225.3 2063.24  4314.4 2060.62  4527.9 2060.35
  4781.3 2059.93  4790.9 2059.52  4797.1 2057.94  4840.2 2057.08  4883.3 2054.15
  4906.3 2051.33  4922.3 2051.21  4973.8 2049.24  4987.1 2048.04  4990.7 2045.52
  4991.2 2045.02  5000.0 2045.52  5003.3 2045.52  5011.0 2049.57  5053.3 2049.92
  5117.9 2057.20  5124.1 2056.27  5160.9 2059.15  5274.2 2056.61  5303.3 2056.94
  5311.9 2058.01  5347.1 2059.74  5367.9 2059.50  5503.4 2066.45  5510.7 2065.94
#Mann=6,-1,0
  4086.8   0.035       0  4527.9    0.07       0  4922.3    0.16       0
  4990.7    0.07       0  5000.0    0.16       0  5311.9    0.07       0
Bank Sta=4990.7,5000
Exp/Cntr=0.3,0.1

Type RM Length L Ch R = 1,17350,782,782,782
BEGIN DESCRIPTION:
Plum Creek 21.0
END DESCRIPTION:
XS GIS Cut Line= 3
      1418625.36      6858046.95      1419279.21      6858211.34
      1419796.50      6858207.18
#Sta/Elev= 30
  4325.8 2057.00  4330.7 2056.95  4449.2 2056.78  4490.4 2057.55  4504.4 2056.88
  4674.8 2056.32  4798.2 2057.42  4811.5 2058.30  4880.4 2055.37  4912.8 2052.17
  4921.6 2050.44  4962.7 2045.94  4975.0 2046.12  5001.0 2045.00  5001.5 2044.50
  5010.5 2045.00  5015.8 2047.09  5025.8 2048.37  5045.8 2048.06  5125.8 2050.32
  5155.8 2051.91  5174.9 2053.85  5215.8 2055.40  5255.8 2058.88  5329.4 2062.86
  5355.8 2065.01  5405.8 2065.86  5455.8 2068.84  5495.8 2069.30  5517.3 2070.45
#Mann=9,-1,0
  4325.8   0.035       0  4330.7    0.07       0  4504.4   0.035       0
  4811.5    0.07       0  4912.8    0.16       0  5001.0    0.07       0
  5010.5    0.16       0  5174.9    0.07       0  5329.4   0.035       0
Bank Sta=5001,5010.5
Exp/Cntr=0.3,0.1

Type RM Length L Ch R = 1,16568,499,499,499
BEGIN DESCRIPTION:
Plum Creek 20.0
END DESCRIPTION:
XS GIS Cut Line= 3
      1418804.99      6858187.96      1418904.91      6858813.02
      1419705.00      6858738.00
#Sta/Elev= 30
  4367.0 2057.06  4407.5 2055.48  4499.3 2056.10  4620.2 2054.37  4845.1 2053.75
  4883.5 2051.79  4913.9 2043.46  4924.0 2043.24  4934.2 2040.01  4944.3 2041.74
  4969.9 2039.21  4970.4 2038.71  4979.5 2039.21  4994.9 2040.02  5000.0 2044.04
  5002.7 2040.02  5030.2 2040.65  5050.3 2042.87  5070.4 2043.38  5106.5 2047.66
  5111.5 2046.72  5180.9 2052.11  5210.2 2052.54  5271.3 2049.29  5324.1 2048.49
  5391.8 2051.86  5442.0 2055.84  5571.3 2058.91  5640.4 2062.36  5803.6 2068.10
#Mann=5,-1,0
  4367.0   0.035       0  4499.3    0.07       0  4969.9    0.07       0
  4979.5    0.07       0  5571.3   0.035       0
Bank Sta=4969.9,4979.5
Exp/Cntr=0.3,0.1

Type RM Length L Ch R = 1,16069,990,990,990
BEGIN DESCRIPTION:
Plum Creek 19.0
END DESCRIPTION:
XS GIS Cut Line= 3
      1417855.04      6859437.99      1418675.17      6859218.07
      1419854.96      6858838.01
#Sta/Elev= 30
  4150.9 2064.60  4248.1 2059.43  4451.1 2051.56  4592.9 2043.36  4632.9 2041.77
  4638.1 2042.92  4659.6 2040.24  4773.1 2039.20  4787.7 2038.58  4788.1 2037.19
  4788.6 2036.69  4797.8 2037.19  4803.1 2039.31  4844.5 2043.16  4896.3 2045.18
  4937.4 2044.22  4942.6 2046.79  4948.1 2046.91  4968.8 2044.79  4977.5 2041.36
  4982.6 2043.77  5010.3 2038.11  5016.1 2039.57  5062.9 2039.00  5240.5 2049.02
  5724.7 2052.67  6009.3 2061.92  6122.1 2067.36  6208.0 2069.13  6239.5 2071.87
#Mann=7,-1,0
  4150.9   0.035       0  4248.1    0.07       0  4659.6   0.035       0
  4773.1    0.07       0  4788.1    0.07       0  4797.8    0.07       0
  6009.3   0.035       0
Bank Sta=4788.1,4797.8
Exp/Cntr=0.3,0.1

Type RM Length L Ch R = 1,15079,498,498,498
BEGIN DESCRIPTION:
Plum Creek 18.0
END DESCRIPTION:
XS GIS Cut Line= 3
      1418204.99      6860088.00      1418316.33      6860028.16
      1419704.96      6859188.02
#Sta/Elev= 30
  4873.6 2051.83  4887.4 2051.69  4903.6 2048.58  4909.3 2049.54  4925.6 2046.12
  4931.2 2047.04  4941.7 2045.29  4947.5 2042.91  4963.7 2040.74  4969.4 2041.32
  4975.8 2037.65  4984.3 2035.82  5007.5 2033.56  5008.0 2033.06  5018.4 2033.56
  5028.5 2035.19  5040.2 2035.01  5071.2 2034.84  5086.7 2037.10  5218.6 2036.34
  5275.7 2037.98  5285.3 2038.49  5304.0 2040.87  5377.7 2044.12  5435.2 2043.33
  5490.2 2043.29  5721.0 2045.56  6165.2 2046.39  6425.2 2051.12  6623.0 2056.86
#Mann=9,-1,0
  4873.6    0.07       0  4984.3   0.035       0  5007.5   0.035       0
  5018.4   0.035       0  5040.2    0.07       0  5275.7    0.16       0
  5285.3    0.07       0  5435.2    0.16       0  5490.2    0.07       0
Bank Sta=5007.5,5018.4
Exp/Cntr=0.3,0.1