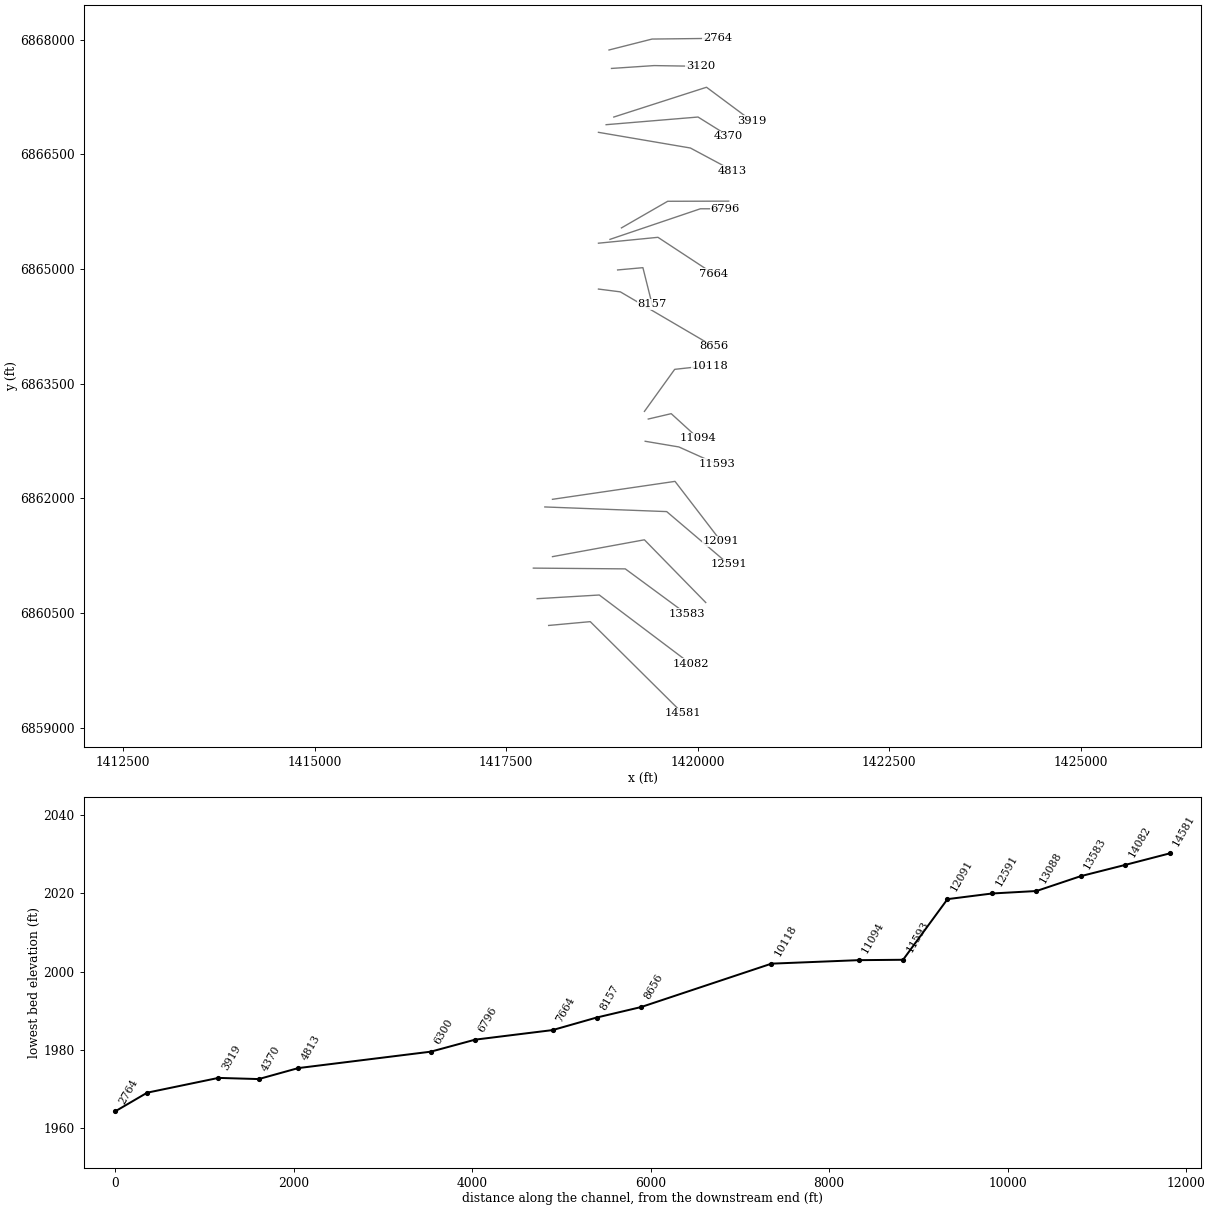
HEC-RAS study Plum Creek.prj: Plum Creek Base Level Engineering

--- Plum Creek.g01 (geometry) --- (continued)

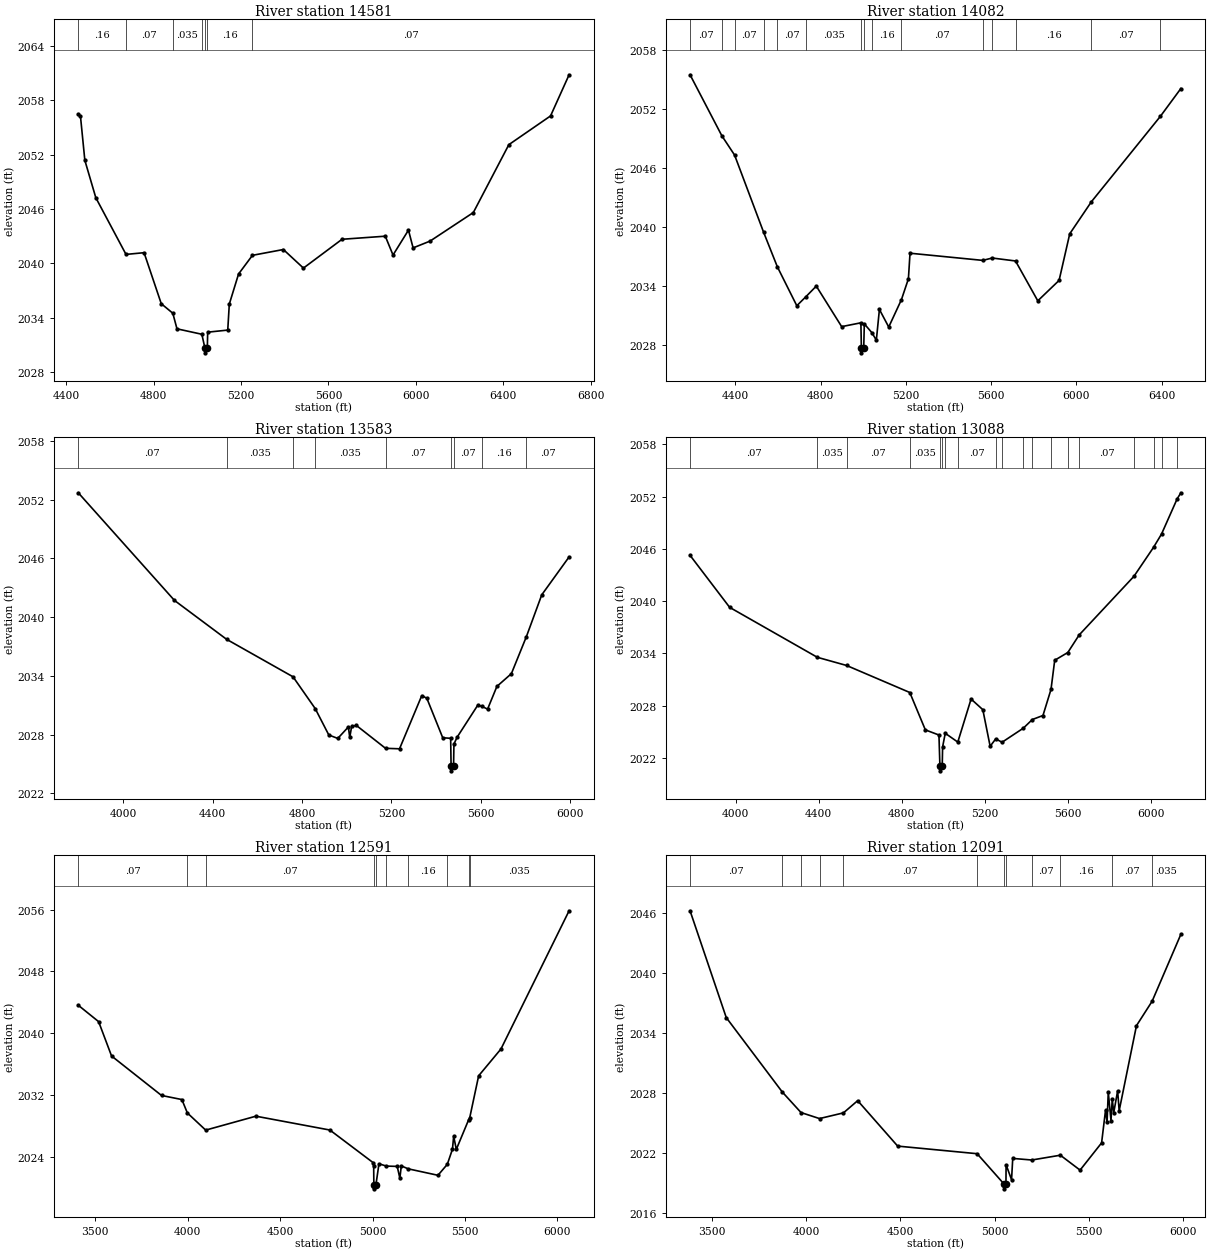
Type RM Length L Ch R = 1,14581,499,499,499
BEGIN DESCRIPTION:
Plum Creek 17.0
END DESCRIPTION:
XS GIS Cut Line= 3
      1418054.98      6860338.00      1418598.00      6860387.78
      1419805.03      6859187.97
#Sta/Elev= 30
  4454.7 2056.46  4464.8 2056.22  4484.8 2051.36  4535.1 2047.23  4673.3 2040.98
  4756.0 2041.17  4834.7 2035.54  4887.6 2034.49  4906.6 2032.77  5020.5 2032.17
  5034.7 2030.62  5035.2 2030.12  5045.6 2030.62  5047.2 2032.40  5139.1 2032.63
  5146.2 2035.50  5188.6 2038.82  5252.2 2040.88  5393.7 2041.52  5485.6 2039.47
  5662.4 2042.65  5860.4 2042.99  5895.8 2040.91  5966.5 2043.66  5987.7 2041.70
  6065.5 2042.45  6263.5 2045.60  6426.1 2053.09  6617.0 2056.26  6701.9 2060.80
#Mann=7,-1,0
  4454.7    0.16       0  4673.3    0.07       0  4887.6   0.035       0
  5020.5    0.16       0  5034.7   0.035       0  5045.6    0.16       0
  5252.2    0.07       0
Bank Sta=5034.7,5045.6
Exp/Cntr=0.3,0.1

Type RM Length L Ch R = 1,14082,499,499,499
BEGIN DESCRIPTION:
Plum Creek 16.0
END DESCRIPTION:
XS GIS Cut Line= 3
      1417905.04      6860688.00      1418715.70      6860736.30
      1419904.98      6859838.02
#Sta/Elev= 30
  4187.9 2055.51  4337.2 2049.29  4396.8 2047.33  4532.7 2039.48  4597.3 2035.95
  4688.7 2031.98  4732.3 2032.92  4780.1 2033.98  4899.1 2029.85  4989.3 2030.24
  4991.6 2027.68  4992.1 2027.18  5002.6 2027.68  5005.4 2030.13  5040.7 2029.24
  5061.8 2028.47  5076.2 2031.60  5119.9 2029.81  5179.5 2032.60  5212.2 2034.72
  5219.8 2037.33  5560.8 2036.60  5605.5 2036.84  5714.7 2036.54  5819.2 2032.48
  5919.1 2034.56  5969.1 2039.31  6070.5 2042.57  6393.7 2051.26  6490.4 2054.11
#Mann=15,-1,0
  4187.9    0.07       0  4337.2    0.16       0  4396.8    0.07       0
  4532.7    0.16       0  4597.3    0.07       0  4732.3   0.035       0
  4991.6   0.035       0  5002.6   0.035       0  5040.7    0.16       0
  5179.5    0.07       0  5560.8    0.16       0  5605.5    0.07       0
  5714.7    0.16       0  6070.5    0.07       0  6393.7   0.035       0
Bank Sta=4991.6,5002.6
Exp/Cntr=0.3,0.1

Type RM Length L Ch R = 1,13583,495,495,495
BEGIN DESCRIPTION:
Plum Creek 15.0
END DESCRIPTION:
XS GIS Cut Line= 3
      1417855.00      6861088.00      1419055.16      6861077.94
      1419855.03      6860487.98
#Sta/Elev= 30
  3799.8 2052.70  4229.8 2041.71  4462.8 2037.74  4759.9 2033.91  4858.9 2030.67
  4919.8 2027.97  4959.8 2027.62  5007.2 2028.79  5013.4 2027.72  5021.8 2028.84
  5042.7 2028.95  5173.3 2026.61  5235.9 2026.56  5335.3 2031.99  5358.0 2031.72
  5429.0 2027.69  5464.5 2027.63  5466.4 2024.81  5466.9 2024.31  5477.5 2024.81
  5479.1 2027.05  5493.8 2027.76  5585.6 2031.01  5605.6 2030.88  5629.5 2030.61
  5671.2 2032.93  5735.9 2034.23  5803.0 2038.01  5871.7 2042.28  5993.9 2046.15
#Mann=9,-1,0
  3799.8    0.07       0  4462.8   0.035       0  4759.9    0.07       0
  4858.9   0.035       0  5173.3    0.07       0  5466.4   0.035       0
  5477.5    0.07       0  5605.6    0.16       0  5803.0    0.07       0
Bank Sta=5466.4,5477.5
Exp/Cntr=0.3,0.1

Type RM Length L Ch R = 1,13088,497,497,497
BEGIN DESCRIPTION:
Plum Creek 14.0
END DESCRIPTION:
XS GIS Cut Line= 3
      1418105.05      6861238.01      1419304.58      6861458.35
      1420104.97      6860638.03
#Sta/Elev= 30
  3780.4 2045.26  3971.3 2039.29  4393.8 2033.56  4535.0 2032.62  4839.5 2029.52
  4914.5 2025.23  4980.1 2024.64  4984.7 2021.03  4985.2 2020.53  4995.8 2021.03
  4997.7 2023.28  5010.4 2024.84  5070.9 2023.83  5134.9 2028.77  5191.5 2027.55
  5226.8 2023.35  5253.8 2024.20  5284.2 2023.81  5387.0 2025.43  5430.2 2026.42
  5481.4 2026.88  5520.2 2029.88  5538.0 2033.22  5601.2 2034.11  5655.7 2036.12
  5919.8 2042.85  6014.4 2046.18  6053.0 2047.71  6128.1 2051.74  6146.1 2052.44
#Mann=19,-1,0
  3780.4    0.07       0  4393.8   0.035       0  4535.0    0.07       0
  4839.5   0.035       0  4984.7    0.07       0  4995.8   0.035       0
  5010.4   0.035       0  5070.9    0.07       0  5253.8   0.035       0
  5284.2    0.16       0  5387.0    0.07       0  5430.2    0.16       0
  5520.2    0.07       0  5601.2    0.16       0  5655.7    0.07       0
  5919.8   0.035       0  6014.4    0.07       0  6053.0   0.035       0
  6128.1    0.07       0
Bank Sta=4984.7,4995.8
Exp/Cntr=0.3,0.1

Type RM Length L Ch R = 1,12591,500,500,500
BEGIN DESCRIPTION:
Plum Creek 13.0
END DESCRIPTION:
XS GIS Cut Line= 3
      1418004.99      6861888.00      1419595.33      6861827.20
      1420405.02      6861137.99
#Sta/Elev= 30
  3408.5 2043.63  3518.6 2041.51  3588.6 2037.07  3858.8 2031.97  3968.9 2031.44
  3998.5 2029.71  4097.7 2027.49  4369.2 2029.29  4769.5 2027.50  5003.1 2023.29
  5006.3 2022.86  5007.3 2020.40  5007.8 2019.90  5018.4 2020.40  5034.9 2023.14
  5075.1 2022.84  5133.7 2022.80  5148.0 2021.26  5155.7 2022.87  5192.3 2022.49
  5354.1 2021.65  5404.6 2023.07  5432.4 2025.02  5439.0 2026.69  5453.3 2025.00
  5520.0 2028.83  5525.3 2029.03  5574.1 2034.51  5694.9 2037.98  6063.3 2055.84
#Mann=10,-1,0
  3408.5    0.07       0  3998.5   0.035       0  4097.7    0.07       0
  5007.3    0.07       0  5018.4    0.07       0  5075.1    0.07       0
  5192.3    0.16       0  5404.6    0.07       0  5520.0    0.16       0
  5525.3   0.035       0
Bank Sta=5007.3,5018.4
Exp/Cntr=0.3,0.1

Type RM Length L Ch R = 1,12091,498,498,498
BEGIN DESCRIPTION:
Plum Creek 12.0
END DESCRIPTION:
XS GIS Cut Line= 3
      1418104.97      6861988.00      1419704.05      6862222.61
      1420305.00      6861438.01
#Sta/Elev= 30
  3383.8 2046.24  3575.9 2035.57  3873.0 2028.14  3972.7 2026.08  4070.8 2025.48
  4197.8 2026.05  4273.3 2027.27  4485.5 2022.73  4907.2 2021.97  5049.0 2018.96
  5049.5 2018.46  5060.1 2018.96  5060.8 2020.87  5089.8 2019.37  5096.1 2021.50
  5197.2 2021.34  5348.7 2021.82  5453.4 2020.33  5567.6 2023.05  5588.5 2026.31
  5596.7 2025.14  5603.0 2028.12  5617.5 2025.28  5624.1 2027.41  5632.0 2026.07
  5652.8 2028.26  5660.8 2026.26  5752.6 2034.76  5835.7 2037.20  5988.3 2043.89
#Mann=12,-1,0
  3383.8    0.07       0  3873.0   0.035       0  3972.7    0.07       0
  4070.8    0.16       0  4197.8    0.07       0  4907.2    0.16       0
  5049.0    0.07       0  5060.1    0.16       0  5197.2    0.07       0
  5348.7    0.16       0  5624.1    0.07       0  5835.7   0.035       0
Bank Sta=5049,5060.1
Exp/Cntr=0.3,0.1

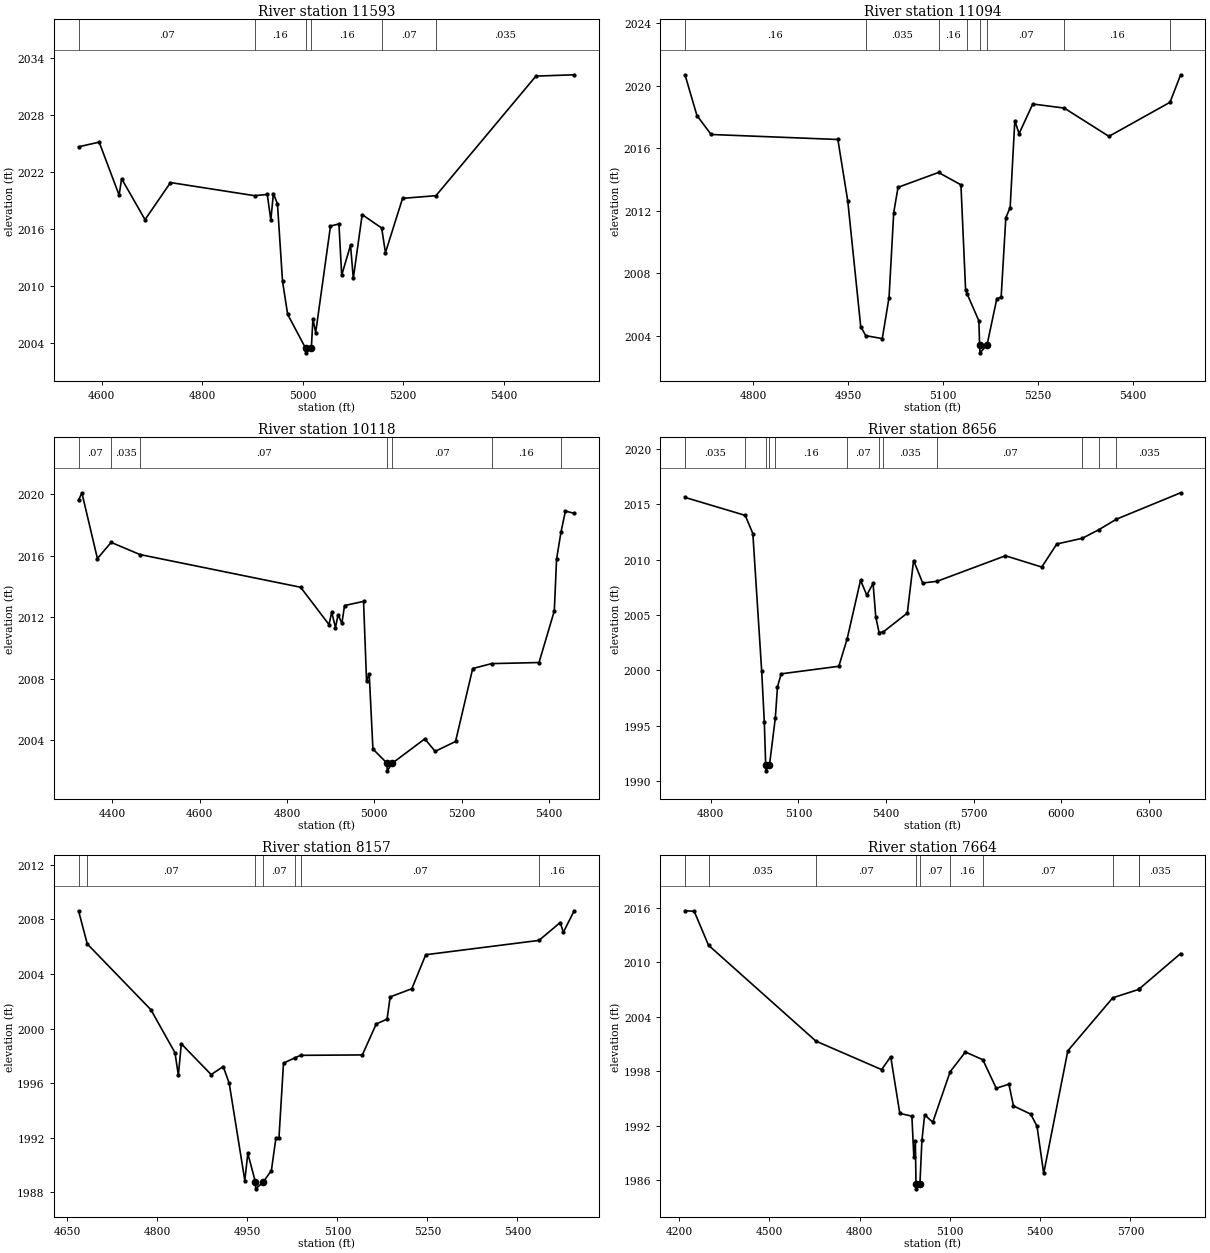
Type RM Length L Ch R = 1,11593,499,499,499
BEGIN DESCRIPTION:
Plum Creek 11.0
END DESCRIPTION:
XS GIS Cut Line= 3
      1419314.65      6862747.12      1419754.51      6862672.78
      1420247.44      6862450.81
#Sta/Elev= 30
  4553.9 2024.66  4594.8 2025.15  4634.5 2019.58  4639.5 2021.30  4686.1 2017.00
  4736.8 2020.90  4904.2 2019.52  4929.5 2019.65  4936.6 2016.97  4941.7 2019.74
  4949.8 2018.66  4959.9 2010.51  4970.1 2007.05  5005.7 2003.50  5006.2 2003.00
  5017.3 2003.50  5020.4 2006.59  5025.9 2005.12  5055.4 2016.33  5072.2 2016.55
  5077.7 2011.16  5095.3 2014.32  5100.8 2010.82  5118.5 2017.53  5157.3 2016.12
  5164.8 2013.53  5198.9 2019.24  5265.4 2019.52  5464.4 2032.09  5540.6 2032.23
#Mann=6,-1,0
  4553.9    0.07       0  4904.2    0.16       0  5005.7    0.07       0
  5017.3    0.16       0  5157.3    0.07       0  5265.4   0.035       0
Bank Sta=5005.7,5017.3
Exp/Cntr=0.3,0.1

Type RM Length L Ch R = 1,11094,976,976,976
BEGIN DESCRIPTION:
Plum Creek 10.0
END DESCRIPTION:
XS GIS Cut Line= 3
      1419355.00      6863038.00      1419654.48      6863108.21
      1420005.03      6862787.97
#Sta/Elev= 30
  4692.4 2020.67  4711.1 2018.08  4733.5 2016.87  4933.6 2016.55  4949.2 2012.62
  4969.7 2004.58  4977.6 2004.00  5003.7 2003.81  5014.4 2006.44  5021.8 2011.87
  5028.6 2013.49  5092.5 2014.44  5127.9 2013.65  5135.3 2006.92  5137.6 2006.68
  5156.2 2004.95  5157.4 2003.40  5157.9 2002.90  5169.1 2003.40  5184.6 2006.37
  5191.4 2006.46  5198.8 2011.55  5205.6 2012.19  5213.0 2017.75  5219.7 2016.92
  5241.3 2018.82  5291.0 2018.56  5361.6 2016.75  5458.0 2018.93  5474.8 2020.69
#Mann=8,-1,0
  4692.4    0.16       0  4977.6   0.035       0  5092.5    0.16       0
  5137.6    0.07       0  5157.4   0.035       0  5169.1    0.07       0
  5291.0    0.16       0  5458.0    0.07       0
Bank Sta=5157.4,5169.1
Exp/Cntr=0.3,0.1

Type RM Length L Ch R = 1,10118,1462,1462,1462
BEGIN DESCRIPTION:
Plum Creek 9.0
END DESCRIPTION:
XS GIS Cut Line= 3
      1419304.98      6863137.97      1419699.87      6863687.87
      1420155.02      6863738.00
#Sta/Elev= 30
  4323.0 2019.63  4330.4 2020.11  4366.0 2015.83  4397.5 2016.88  4463.4 2016.09
  4831.4 2013.96  4896.4 2011.53  4902.6 2012.34  4911.2 2011.34  4917.3 2012.18
  4925.9 2011.61  4932.0 2012.77  4975.5 2013.04  4982.4 2007.87  4988.5 2008.31
  4997.0 2003.43  5029.2 2002.51  5029.7 2002.01  5041.5 2002.51  5115.8 2004.09
  5139.6 2003.28  5186.2 2003.92  5225.5 2008.67  5268.9 2008.99  5377.4 2009.06
  5412.4 2012.42  5417.6 2015.80  5427.8 2017.56  5437.8 2018.92  5457.9 2018.77
#Mann=7,-1,0
  4323.0    0.07       0  4397.5   0.035       0  4463.4    0.07       0
  5029.2    0.07       0  5041.5    0.07       0  5268.9    0.16       0
  5427.8   0.035       0
Bank Sta=5029.2,5041.5
Exp/Cntr=0.3,0.1

Type RM Length L Ch R = 1,8656,499,499,499
BEGIN DESCRIPTION:
Plum Creek 8.0
END DESCRIPTION:
XS GIS Cut Line= 3
      1418704.96      6864738.00      1418990.63      6864701.38
      1420204.99      6863988.01
#Sta/Elev= 30
  4712.0 2015.60  4917.9 2013.98  4943.9 2012.34  4974.2 1999.94  4983.2 1995.33
  4987.9 1991.44  4988.4 1990.94  5000.8 1991.44  5021.0 1995.75  5028.3 1998.52
  5041.0 1999.69  5238.3 2000.37  5266.9 2002.86  5312.6 2008.13  5334.0 2006.79
  5355.5 2007.85  5364.6 2004.85  5376.0 2003.41  5390.4 2003.47  5472.7 2005.17
  5494.2 2009.91  5525.5 2007.88  5575.1 2008.04  5808.7 2010.34  5932.9 2009.32
  5984.5 2011.40  6072.1 2011.92  6129.0 2012.70  6188.8 2013.64  6408.4 2016.02
#Mann=12,-1,0
  4712.0   0.035       0  4917.9    0.07       0  4987.9    0.07       0
  5000.8    0.07       0  5021.0    0.16       0  5266.9    0.07       0
  5376.0    0.16       0  5390.4   0.035       0  5575.1    0.07       0
  6072.1   0.035       0  6129.0    0.07       0  6188.8   0.035       0
Bank Sta=4987.9,5000.8
Exp/Cntr=0.3,0.1

Type RM Length L Ch R = 1,8157,493,493,493
BEGIN DESCRIPTION:
Plum Creek 7.0
END DESCRIPTION:
XS GIS Cut Line= 3
      1418955.03      6864988.00      1419285.08      6865017.82
      1419405.01      6864537.98
#Sta/Elev= 30
  4668.6 2008.61  4683.0 2006.20  4789.1 2001.38  4829.2 1998.23  4834.8 1996.59
  4839.8 1998.88  4889.5 1996.63  4909.6 1997.22  4919.6 1995.99  4945.6 1988.87
  4950.6 1990.85  4963.3 1988.76  4963.8 1988.26  4976.3 1988.76  4989.9 1989.60
  4997.4 1991.97  5002.5 1991.97  5010.1 1997.47  5029.7 1997.87  5038.8 1998.04
  5141.5 1998.07  5164.7 2000.34  5182.7 2000.69  5187.9 2002.32  5224.0 2002.92
  5247.2 2005.41  5435.9 2006.46  5471.4 2007.77  5476.5 2007.05  5494.6 2008.63
#Mann=7,-1,0
  4668.6   0.035       0  4683.0    0.07       0  4963.3    0.07       0
  4976.3    0.07       0  5029.7    0.16       0  5038.8    0.07       0
  5435.9    0.16       0
Bank Sta=4963.3,4976.3
Exp/Cntr=0.3,0.1

Type RM Length L Ch R = 1,7664,868,868,868
BEGIN DESCRIPTION:
Plum Creek 6.0
END DESCRIPTION:
XS GIS Cut Line= 3
      1418704.98      6865338.00      1419481.29      6865414.82
      1420205.03      6864937.98
#Sta/Elev= 30
  4219.9 2015.65  4250.1 2015.60  4297.7 2011.86  4654.5 2001.32  4873.1 1998.18
  4903.2 1999.61  4933.4 1993.37  4973.6 1993.06  4980.1 1988.53  4985.1 1990.30
  4987.2 1985.57  4987.7 1985.07  5000.2 1985.57  5006.9 1990.40  5016.0 1993.20
  5043.0 1992.40  5100.6 1997.94  5151.4 2000.12  5209.3 1999.27  5253.9 1996.13
  5296.0 1996.58  5311.1 1994.19  5368.3 1993.29  5389.3 1991.97  5411.6 1986.77
  5491.8 2000.25  5641.2 2006.08  5727.2 2007.00  5728.1 2007.03  5866.7 2010.95
#Mann=10,-1,0
  4219.9    0.07       0  4297.7   0.035       0  4654.5    0.07       0
  4987.2    0.07       0  5000.2    0.07       0  5100.6    0.16       0
  5209.3    0.07       0  5641.2   0.035       0  5727.2    0.07       0
  5728.1   0.035       0
Bank Sta=4987.2,5000.2
Exp/Cntr=0.3,0.1

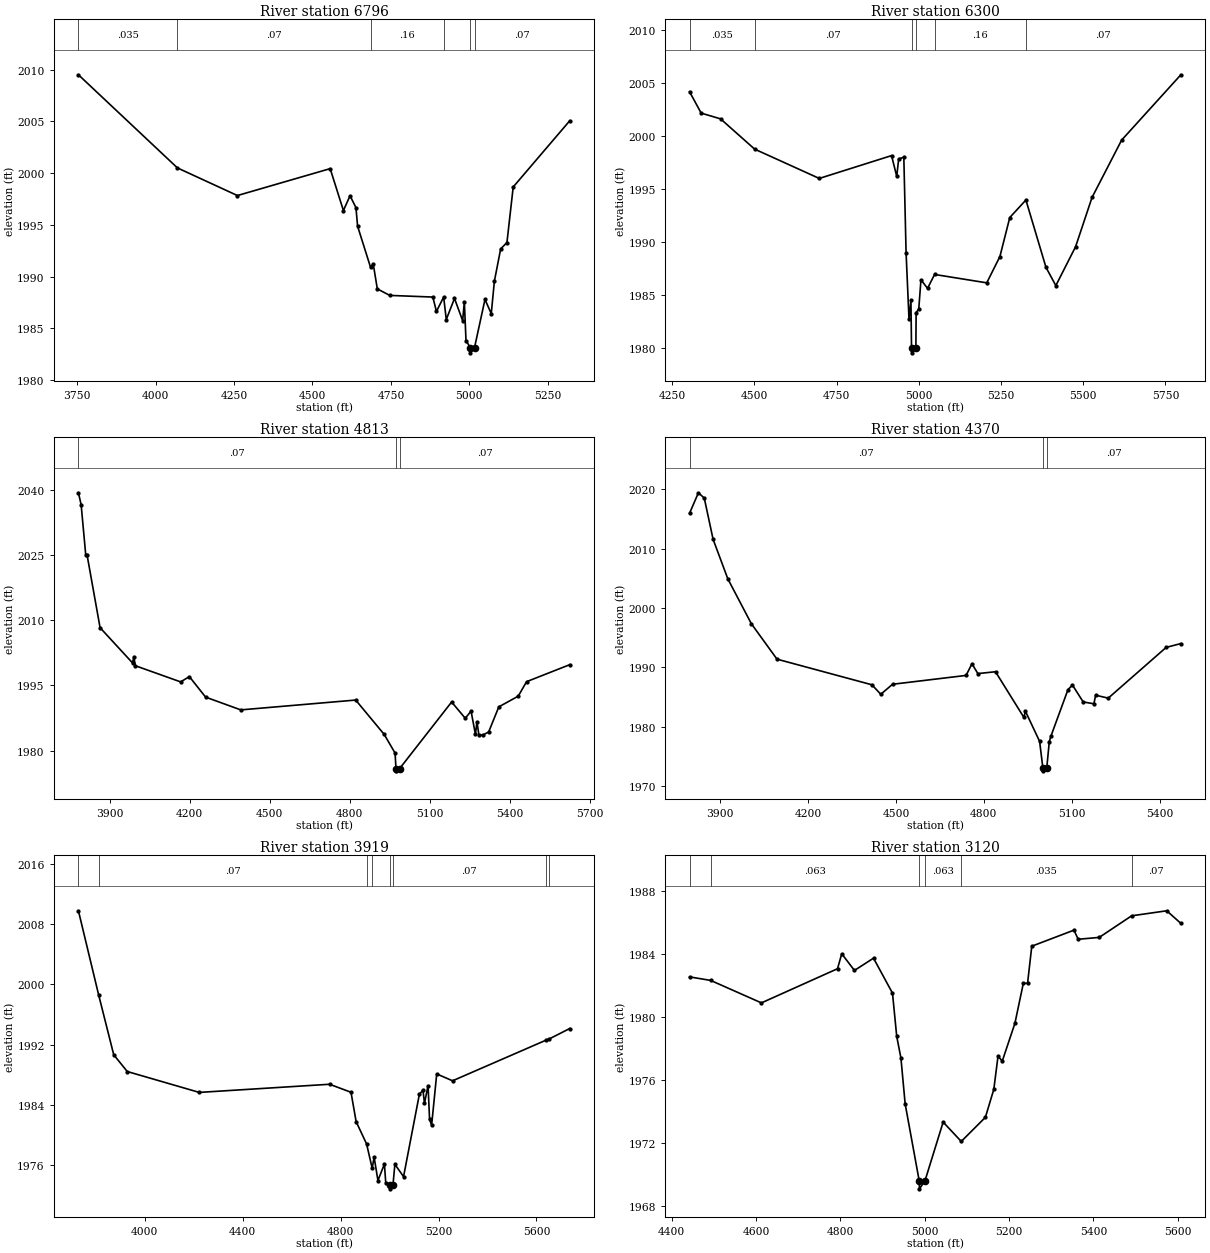
Type RM Length L Ch R = 1,6796,496,496,496
BEGIN DESCRIPTION:
Plum Creek 5.0
END DESCRIPTION:
XS GIS Cut Line= 3
      1418855.02      6865388.01      1420035.15      6865788.09
      1420355.05      6865788.00
#Sta/Elev= 30
  3753.9 2009.50  4069.5 2000.50  4260.7 1997.83  4556.4 2000.43  4598.6 1996.38
  4619.7 1997.81  4638.6 1996.66  4643.8 1994.87  4685.2 1990.89  4693.6 1991.24
  4706.7 1988.81  4746.4 1988.18  4883.7 1988.02  4895.1 1986.63  4918.2 1988.02
  4926.5 1985.85  4952.7 1987.89  4978.7 1985.74  4984.1 1987.56  4989.4 1983.82
  5003.2 1983.13  5003.7 1982.63  5016.5 1983.13  5049.9 1987.79  5069.9 1986.42
  5079.9 1989.56  5099.9 1992.67  5119.9 1993.29  5139.9 1998.66  5319.9 2005.05
#Mann=6,-1,0
  3753.9   0.035       0  4069.5    0.07       0  4685.2    0.16       0
  4918.2    0.07       0  5003.2    0.07       0  5016.5    0.07       0
Bank Sta=5003.2,5016.5
Exp/Cntr=0.3,0.1

Type RM Length L Ch R = 1,6300,1487,1487,1487
BEGIN DESCRIPTION:
Plum Creek 4.0
END DESCRIPTION:
XS GIS Cut Line= 3
      1419005.00      6865538.00      1419608.32      6865886.22
      1420405.02      6865888.00
#Sta/Elev= 30
  4303.4 2004.15  4338.6 2002.14  4397.5 2001.60  4501.1 1998.75  4697.6 1995.99
  4917.3 1998.14  4933.1 1996.18  4938.9 1997.82  4954.6 1997.99  4961.5 1988.98
  4970.4 1982.71  4976.2 1984.53  4978.0 1980.07  4978.5 1979.57  4991.3 1980.07
  4992.0 1983.36  5000.0 1983.69  5006.7 1986.45  5026.7 1985.64  5048.1 1986.95
  5206.7 1986.16  5246.7 1988.64  5276.7 1992.31  5325.7 1993.96  5386.7 1987.62
  5416.7 1985.90  5476.7 1989.56  5526.7 1994.20  5616.7 1999.60  5796.7 2005.75
#Mann=6,-1,0
  4303.4   0.035       0  4501.1    0.07       0  4978.0    0.07       0
  4991.3    0.07       0  5048.1    0.16       0  5325.7    0.07       0
Bank Sta=4978,4991.3
Exp/Cntr=0.3,0.1

Type RM Length L Ch R = 1,4813,443,443,443
BEGIN DESCRIPTION:
Plum Creek 3.0
END DESCRIPTION:
XS GIS Cut Line= 3
      1418704.99      6866788.00      1419904.90      6866582.96
      1420455.01      6866287.99
#Sta/Elev= 30
  3782.7 2039.25  3792.9 2036.52  3810.2 2024.93  3815.3 2024.91  3863.9 2008.26
  3985.5 2000.17  3990.6 2001.62  3995.7 1999.53  4165.9 1995.81  4198.6 1997.02
  4259.5 1992.31  4391.4 1989.38  4822.1 1991.64  4929.1 1983.73  4969.7 1979.46
  4973.1 1975.88  4973.6 1975.38  4986.5 1975.88  5181.7 1991.19  5232.7 1987.46
  5254.6 1989.09  5270.9 1983.76  5276.6 1986.67  5283.8 1983.66  5298.5 1983.60
  5320.4 1984.30  5358.6 1990.08  5431.3 1992.53  5462.6 1995.86  5624.2 1999.76
#Mann=3,-1,0
  3782.7    0.07       0  4973.1    0.07       0  4986.5    0.07       0
Bank Sta=4973.1,4986.5
Exp/Cntr=0.3,0.1

Type RM Length L Ch R = 1,4370,451,451,451
BEGIN DESCRIPTION:
Plum Creek 2.0
END DESCRIPTION:
XS GIS Cut Line= 3
      1418805.04      6866888.00      1420004.67      6866988.14
      1420405.04      6866737.98
#Sta/Elev= 30
  3796.2 2016.00  3826.3 2019.44  3846.3 2018.54  3876.4 2011.60  3926.6 2004.94
  4006.9 1997.37  4094.4 1991.40  4418.3 1987.08  4448.4 1985.48  4488.6 1987.17
  4739.4 1988.66  4759.5 1990.62  4779.6 1988.97  4839.8 1989.28  4936.7 1981.58
  4941.7 1982.64  4990.3 1977.54  5001.3 1973.08  5001.8 1972.58  5014.7 1973.08
  5023.3 1977.51  5029.2 1978.47  5087.0 1986.26  5102.3 1987.04  5138.9 1984.19
  5175.5 1983.88  5181.4 1985.33  5224.4 1984.83  5421.9 1993.38  5472.1 1994.03
#Mann=3,-1,0
  3796.2    0.07       0  5001.3    0.07       0  5014.7    0.07       0
Bank Sta=5001.3,5014.7
Exp/Cntr=0.3,0.1

Type RM Length L Ch R = 1,3919,799,799,799
BEGIN DESCRIPTION:
Plum Creek 1.0
END DESCRIPTION:
XS GIS Cut Line= 3
      1418905.02      6866988.01      1420115.24      6867377.65
      1420705.00      6866938.00
#Sta/Elev= 30
  3728.6 2009.76  3811.4 1998.58  3872.9 1990.66  3928.2 1988.44  4222.3 1985.67
  4754.6 1986.75  4842.2 1985.69  4863.2 1981.79  4905.8 1978.84  4928.7 1975.63
  4936.7 1977.07  4952.3 1973.98  4978.7 1976.17  4984.4 1973.59  5000.2 1973.38
  5000.7 1972.88  5013.6 1973.38  5021.5 1976.13  5056.9 1974.50  5121.6 1985.43
  5136.2 1985.96  5142.4 1984.24  5157.0 1986.58  5163.2 1982.08  5171.6 1981.32
  5192.4 1988.12  5257.1 1987.21  5636.9 1992.57  5652.6 1992.77  5735.6 1994.14
#Mann=8,-1,0
  3728.6   0.035       0  3811.4    0.07       0  4905.8    0.16       0
  4928.7    0.07       0  5000.2    0.07       0  5013.6    0.07       0
  5636.9   0.035       0  5652.6    0.07       0
Bank Sta=5000.2,5013.6
Exp/Cntr=0.3,0.1

Type RM Length L Ch R = 1,3120,356,356,356
BEGIN DESCRIPTION:
Plum Creek 3957
END DESCRIPTION:
XS GIS Cut Line= 3
      1418875.12      6867623.76      1419431.16      6867661.12
      1420038.39      6867651.35
#Sta/Elev= 30
  4442.7 1982.57  4492.4 1982.35  4613.0 1980.92  4793.4 1983.09  4803.4 1984.04
  4833.5 1982.98  4878.7 1983.76  4923.7 1981.54  4933.7 1978.80  4943.7 1977.42
  4953.7 1974.51  4987.1 1969.61  4987.6 1969.11  5000.6 1969.61  5043.8 1973.35
  5086.7 1972.12  5143.9 1973.65  5163.9 1975.43  5173.9 1977.54  5183.9 1977.22
  5213.9 1979.62  5233.9 1982.17  5243.9 1982.16  5253.9 1984.52  5353.9 1985.54
  5363.9 1984.96  5413.9 1985.08  5490.6 1986.45  5573.9 1986.77  5607.3 1985.97
#Mann=6,-1,0
  4442.7   0.035       0  4492.4   0.063       0  4987.1   0.063       0
  5000.6   0.063       0  5086.7   0.035       0  5490.6    0.07       0
Bank Sta=4987.1,5000.6
Exp/Cntr=0.3,0.1

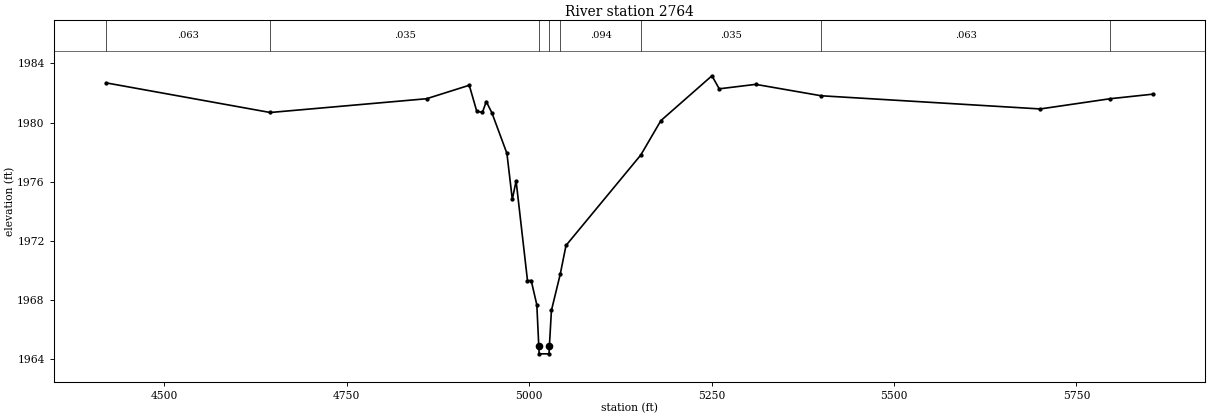
Type RM Length L Ch R = 1,2764,0,0,0
BEGIN DESCRIPTION:
Plum Creek 383
END DESCRIPTION:
XS GIS Cut Line= 3
      1418842.74      6867865.17      1419404.63      6868008.16
      1420259.58      6868017.50
#Sta/Elev= 30
  4420.2 1982.68  4645.0 1980.68  4859.3 1981.61  4917.8 1982.52  4928.1 1980.76
  4935.9 1980.69  4941.1 1981.42  4948.8 1980.66  4969.4 1977.92  4976.8 1974.81
  4982.0 1976.06  4997.6 1969.33  5002.7 1969.33  5010.4 1967.69  5013.1 1964.88
  5013.6 1964.38  5027.1 1964.38  5027.6 1964.88  5030.4 1967.31  5042.5 1969.76
  5050.4 1971.70  5152.9 1977.81  5180.4 1980.13  5250.4 1983.16  5260.4 1982.28
  5310.4 1982.58  5400.1 1981.81  5700.4 1980.92  5796.1 1981.61  5855.0 1981.92
#Mann=8,-1,0
  4420.2   0.063       0  4645.0   0.035       0  5013.1   0.035       0
  5027.6   0.035       0  5042.5   0.094       0  5152.9   0.035       0
  5400.1   0.063       0  5796.1   0.094       0
Bank Sta=5013.1,5027.6
Exp/Cntr=0.3,0.1

Chan Stop Cuts=-1