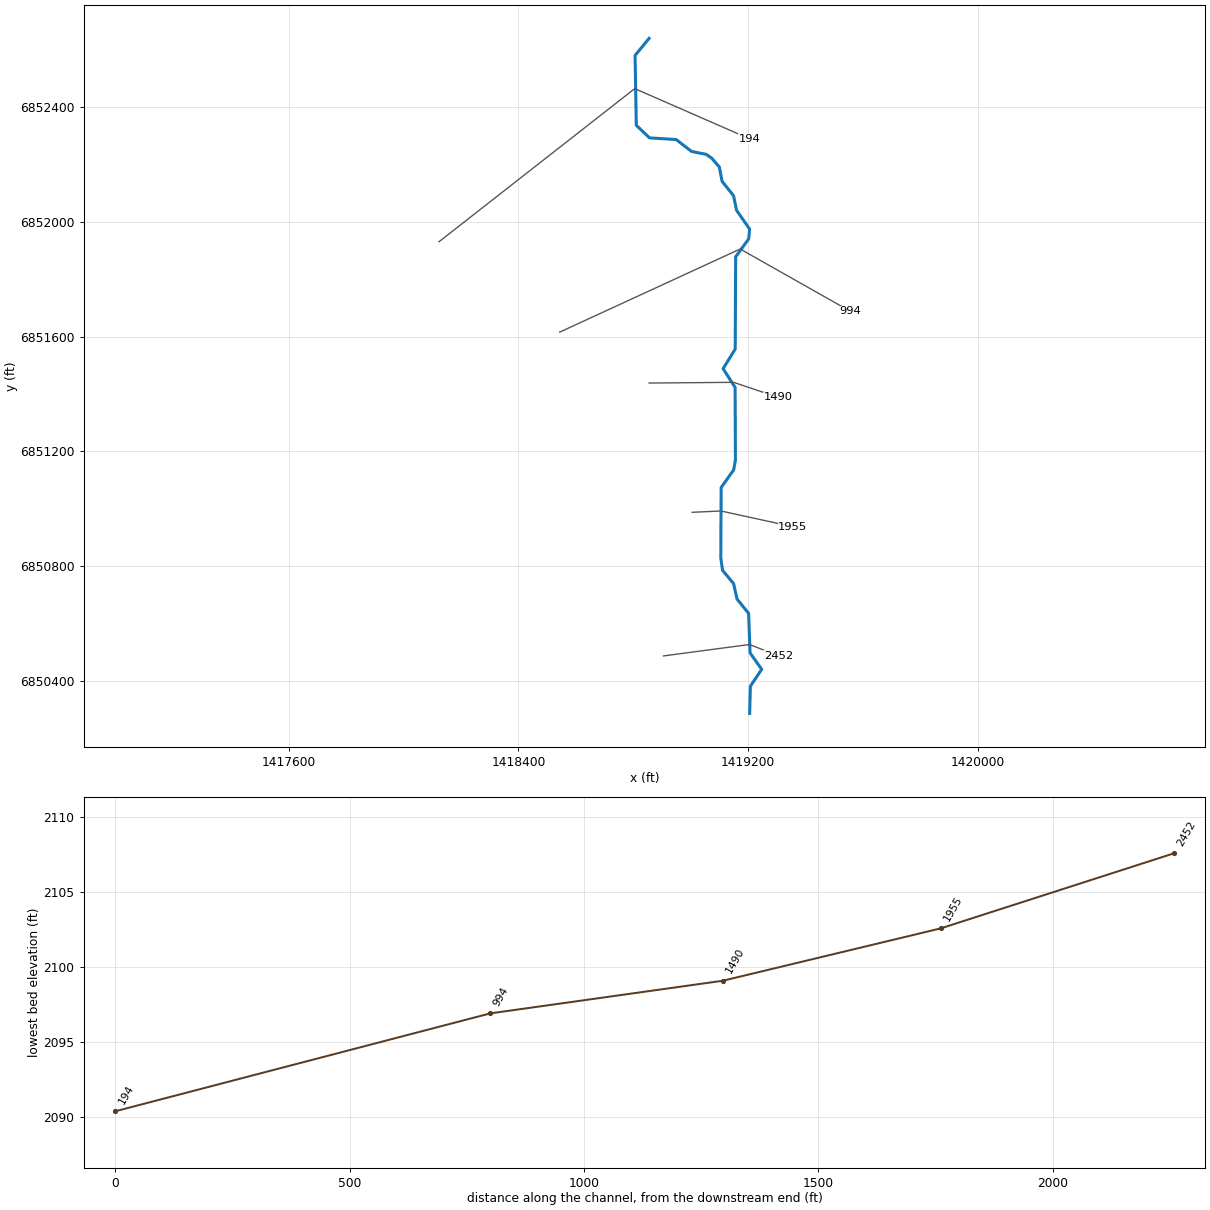
--- Plum Creek Trib.prj (project) ---

Proj Title=Plum Creek Trib Base Level Engineering
Current Plan=p01
Default Exp/Contr=0.3,0.1
English Units
Geom File=g01
Flow File=f01
Plan File=p01
BEGIN DESCRIPTION:
Plum Creek Trib
END DESCRIPTION:

--- Plum Creek Trib.p01 (plan) ---

Plan Title=Multiple Run
Short Identifier=Multiple
Geom File=g01
Flow File=f01
Subcritical Flow
K Sum by GR= 0
Std Step Tol= 0.01
Critical Tol= 0.01
Num of Std Step Trials= 20
Max Error Tol= 0.3
Flow Tol Ratio= 0.001
Split Flow NTrial= 30
Split Flow Tol= 0.02
Split Flow Ratio= 0.02
Log Output Level= 0
Friction Slope Method= 1
Unsteady Friction Slope Method= 2
Unsteady Bridges Friction Slope Method= 1
Parabolic Critical Depth
Global Vel Dist=  1 , 1 , 1
Global Log Level= 0
CheckData=True
Encroach Param= -1, 0, 0, 0
BEGIN DESCRIPTION:
Multiple Run
END DESCRIPTION:

--- Plum Creek Trib.f01 (steady flow) ---

Flow Title=Multiple
Number of Profiles=7
Profile Names=10-year,25-year,50-year,1pct_min,100-year,1pct_plu,500-year
River Rch & RM= Plum Creek Trib,Reach-1,2452
     398     584     746     476     949    1893    1552
River Rch & RM= Plum Creek Trib,Reach-1,1955
     401     586     747     474     945    1886    1534
Boundary for River Rch & Prof#=Plum Creek Trib,Reach-1,1
Up Type=0
Dn Type=3
Dn Slope=0.005
Boundary for River Rch & Prof#=Plum Creek Trib,Reach-1,2
Up Type=0
Dn Type=3
Dn Slope=0.005
Boundary for River Rch & Prof#=Plum Creek Trib,Reach-1,3
Up Type=0
Dn Type=3
Dn Slope=0.005
Boundary for River Rch & Prof#=Plum Creek Trib,Reach-1,4
Up Type=0
Dn Type=3
Dn Slope=0.005
Boundary for River Rch & Prof#=Plum Creek Trib,Reach-1,5
Up Type=0
Dn Type=3
Dn Slope=0.005
Boundary for River Rch & Prof#=Plum Creek Trib,Reach-1,6
Up Type=0
Dn Type=3
Dn Slope=0.005
Boundary for River Rch & Prof#=Plum Creek Trib,Reach-1,7
Up Type=0
Dn Type=3
Dn Slope=0.005

--- Plum Creek Trib.g01 (geometry) ---

Geom Title=Existing Conditions

River Reach=Plum Creek Trib,Reach-1
Reach XY= 30
      1419205.00      6850288.00      1419207.46      6850382.63
      1419246.95      6850441.29      1419206.39      6850498.44
      1419201.24      6850636.44      1419161.12      6850685.82
      1419148.88      6850740.18      1419110.71      6850785.65
      1419104.55      6850828.72      1419105.68      6851074.08
      1419149.25      6851135.67      1419155.39      6851169.66
      1419154.34      6851422.84      1419112.56      6851488.00
      1419154.67      6851556.22      1419156.24      6851877.50
      1419201.63      6851939.74      1419204.77      6851973.91
      1419159.22      6852039.72      1419148.93      6852090.20
      1419109.20      6852139.76      1419099.27      6852190.55
      1419072.06      6852221.52      1419053.58      6852234.14
      1419002.85      6852244.15      1418949.03      6852285.67
      1418856.25      6852291.51      1418810.34      6852335.26
      1418806.10      6852578.45      1418855.00      6852638.00

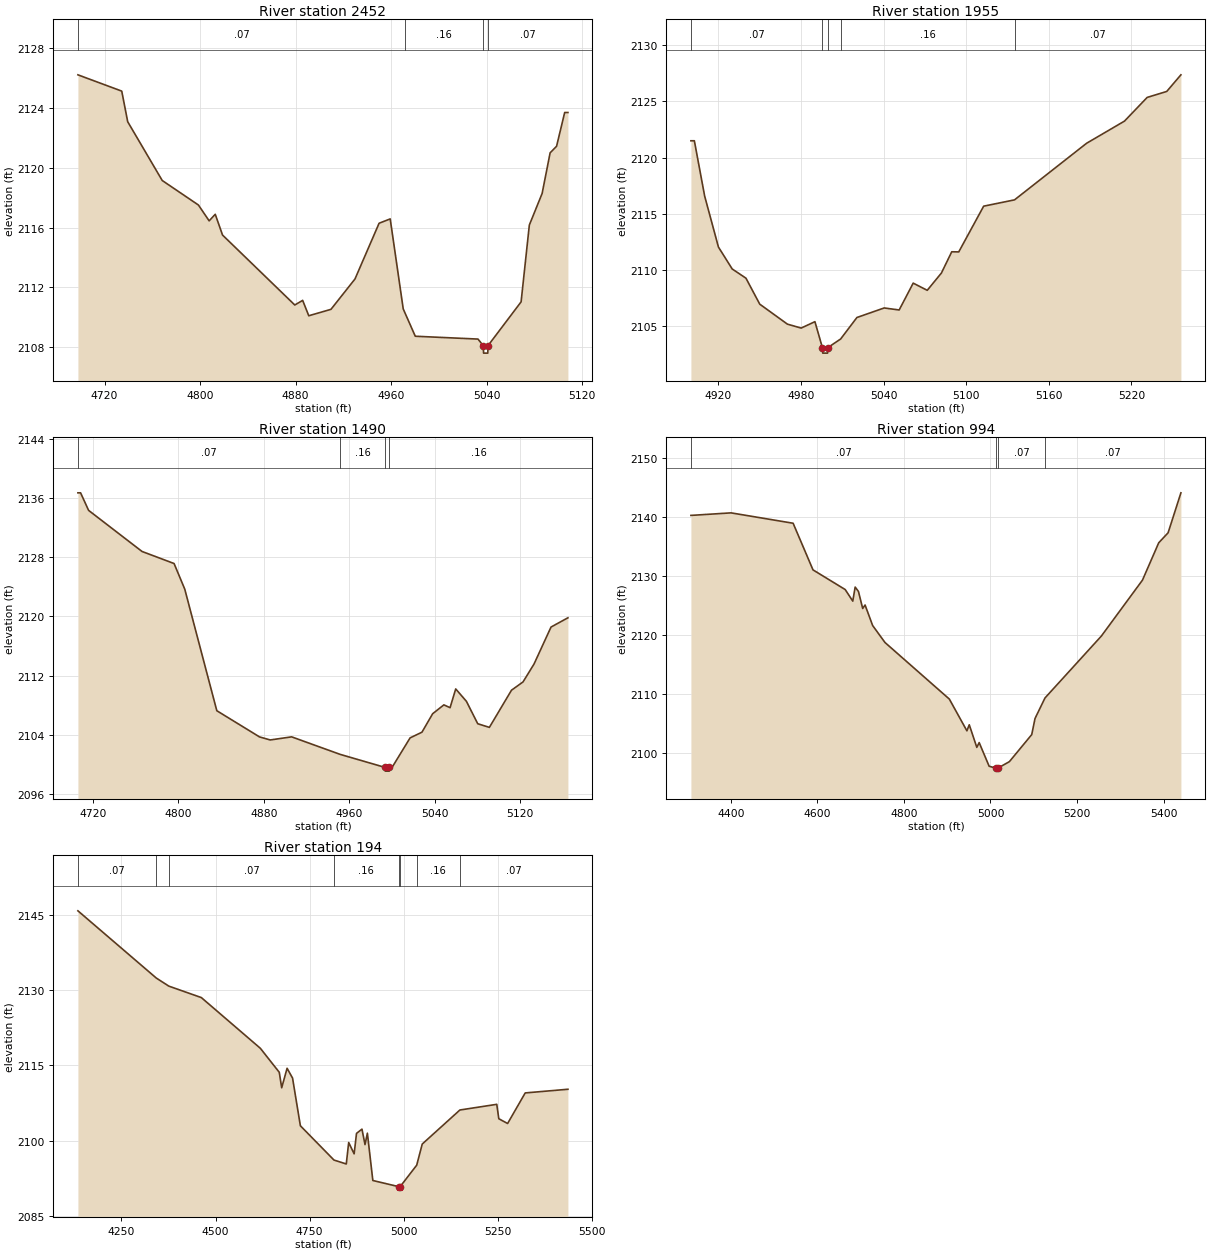
Type RM Length L Ch R = 1,2452,497,497,497
BEGIN DESCRIPTION:
Plum Creek Trib 4.0
END DESCRIPTION:
XS GIS Cut Line= 3
      1418904.98      6850488.00      1419204.65      6850527.81
      1419305.03      6850487.99
#Sta/Elev= 30
  4697.7 2126.22  4734.4 2125.13  4739.4 2123.08  4768.3 2119.15  4798.6 2117.51
  4807.6 2116.45  4812.7 2116.89  4818.8 2115.50  4879.3 2110.82  4885.9 2111.13
  4891.0 2110.10  4909.6 2110.53  4929.7 2112.56  4949.9 2116.29  4959.2 2116.58
  4970.1 2110.56  4971.9 2110.23  4980.2 2108.73  5032.7 2108.54  5037.1 2108.10
  5037.4 2107.60  5040.9 2107.60  5041.1 2108.10  5068.8 2111.03  5075.7 2116.17
  5086.4 2118.28  5093.1 2121.00  5098.5 2121.44  5105.3 2123.70  5108.0 2123.70
#Mann=4,-1,0
  4697.7    0.07       0  4971.9    0.16       0  5037.1    0.07       0
  5041.1    0.07       0
Bank Sta=5037.1,5041.1
Exp/Cntr=0.3,0.1

Type RM Length L Ch R = 1,1955,465,465,465
BEGIN DESCRIPTION:
Plum Creek Trib 3.0
END DESCRIPTION:
XS GIS Cut Line= 3
      1419005.01      6850988.00      1419104.91      6850992.58
      1419355.02      6850938.00
#Sta/Elev= 30
  4900.0 2121.49  4902.5 2121.49  4910.0 2116.56  4920.0 2112.03  4930.0 2110.08
  4940.0 2109.26  4950.0 2106.95  4970.1 2105.17  4980.1 2104.82  4990.1 2105.39
  4995.5 2103.09  4995.8 2102.59  4999.3 2102.59  4999.6 2103.09  5008.8 2103.85
  5020.6 2105.76  5040.4 2106.61  5051.3 2106.43  5061.5 2108.82  5071.7 2108.18
  5082.0 2109.72  5089.5 2111.61  5094.6 2111.60  5112.7 2115.67  5135.1 2116.23
  5187.5 2121.27  5215.0 2123.24  5231.5 2125.35  5245.7 2125.88  5256.0 2127.36
#Mann=5,-1,0
  4900.0    0.07       0  4995.5    0.07       0  4999.6    0.07       0
  5008.8    0.16       0  5135.1    0.07       0
Bank Sta=4995.5,4999.6
Exp/Cntr=0.3,0.1

Type RM Length L Ch R = 1,1490,496,496,496
BEGIN DESCRIPTION:
Plum Creek Trib 2.0
END DESCRIPTION:
XS GIS Cut Line= 3
      1418854.99      6851438.00      1419148.98      6851440.45
      1419305.00      6851388.00
#Sta/Elev= 30
  4706.0 2136.68  4708.5 2136.68  4716.0 2134.31  4766.0 2128.76  4796.0 2127.13
  4806.0 2123.67  4836.0 2107.25  4876.0 2103.71  4886.0 2103.30  4906.0 2103.72
  4951.5 2101.35  4993.5 2099.59  4993.7 2099.09  4997.3 2099.09  4997.6 2099.59
  5000.0 2099.59  5016.9 2103.58  5028.0 2104.35  5038.0 2106.84  5048.5 2108.04
  5054.3 2107.66  5059.6 2110.19  5069.6 2108.52  5080.2 2105.49  5091.1 2105.00
  5111.8 2110.02  5122.6 2111.14  5132.9 2113.56  5148.8 2118.55  5164.6 2119.80
#Mann=4,-1,0
  4706.0    0.07       0  4951.5    0.16       0  4993.5    0.07       0
  4997.6    0.16       0
Bank Sta=4993.5,4997.6
Exp/Cntr=0.3,0.1

Type RM Length L Ch R = 1,994,800,800,800
BEGIN DESCRIPTION:
Plum Creek Trib 1.0
END DESCRIPTION:
XS GIS Cut Line= 3
      1418543.54      6851615.14      1419171.98      6851904.61
      1419554.98      6851688.01
#Sta/Elev= 30
  4308.1 2140.29  4400.9 2140.72  4544.2 2138.96  4590.1 2131.05  4664.5 2127.71
  4682.0 2125.75  4687.5 2128.13  4695.1 2127.39  4704.9 2124.50  4710.4 2125.09
  4727.9 2121.61  4756.4 2118.73  4905.1 2109.13  4945.6 2103.75  4951.1 2104.77
  4968.5 2100.94  4974.0 2101.75  4997.0 2097.74  5012.9 2097.41  5013.2 2096.91
  5017.0 2097.41  5043.8 2098.52  5095.4 2103.11  5103.0 2105.84  5126.0 2109.32
  5256.2 2119.82  5351.2 2129.31  5388.8 2135.65  5410.4 2137.34  5440.0 2144.12
#Mann=4,-1,0
  4308.1    0.07       0  5012.9    0.07       0  5017.0    0.07       0
  5126.0    0.07       0
Bank Sta=5012.9,5017
Exp/Cntr=0.3,0.1

Type RM Length L Ch R = 1,194,0,0,0
BEGIN DESCRIPTION:
Plum Creek Trib 2576
END DESCRIPTION:
XS GIS Cut Line= 3
      1418123.09      6851929.61      1418804.95      6852463.00
      1419205.05      6852287.98
#Sta/Elev= 30
  4134.3 2145.80  4342.6 2132.41  4376.0 2130.80  4462.4 2128.52  4619.2 2118.42
  4669.5 2113.64  4675.9 2110.56  4690.3 2114.44  4704.8 2112.49  4725.6 2102.99
  4814.9 2096.16  4847.6 2095.38  4854.0 2099.66  4868.5 2097.40  4874.8 2101.47
  4889.3 2102.32  4897.4 2099.24  4903.7 2101.51  4918.2 2092.09  4986.6 2090.87
  4986.9 2090.37  4990.8 2090.87  5034.8 2095.14  5049.5 2099.35  5149.6 2106.13
  5247.6 2107.26  5253.0 2104.39  5276.4 2103.44  5323.2 2109.53  5436.7 2110.26
#Mann=8,-1,0
  4134.3    0.07       0  4342.6    0.16       0  4376.0    0.07       0
  4814.9    0.16       0  4986.6    0.07       0  4990.8    0.16       0
  5034.8    0.16       0  5149.6    0.07       0
Bank Sta=4986.6,4990.8
Exp/Cntr=0.3,0.1

Chan Stop Cuts=-1