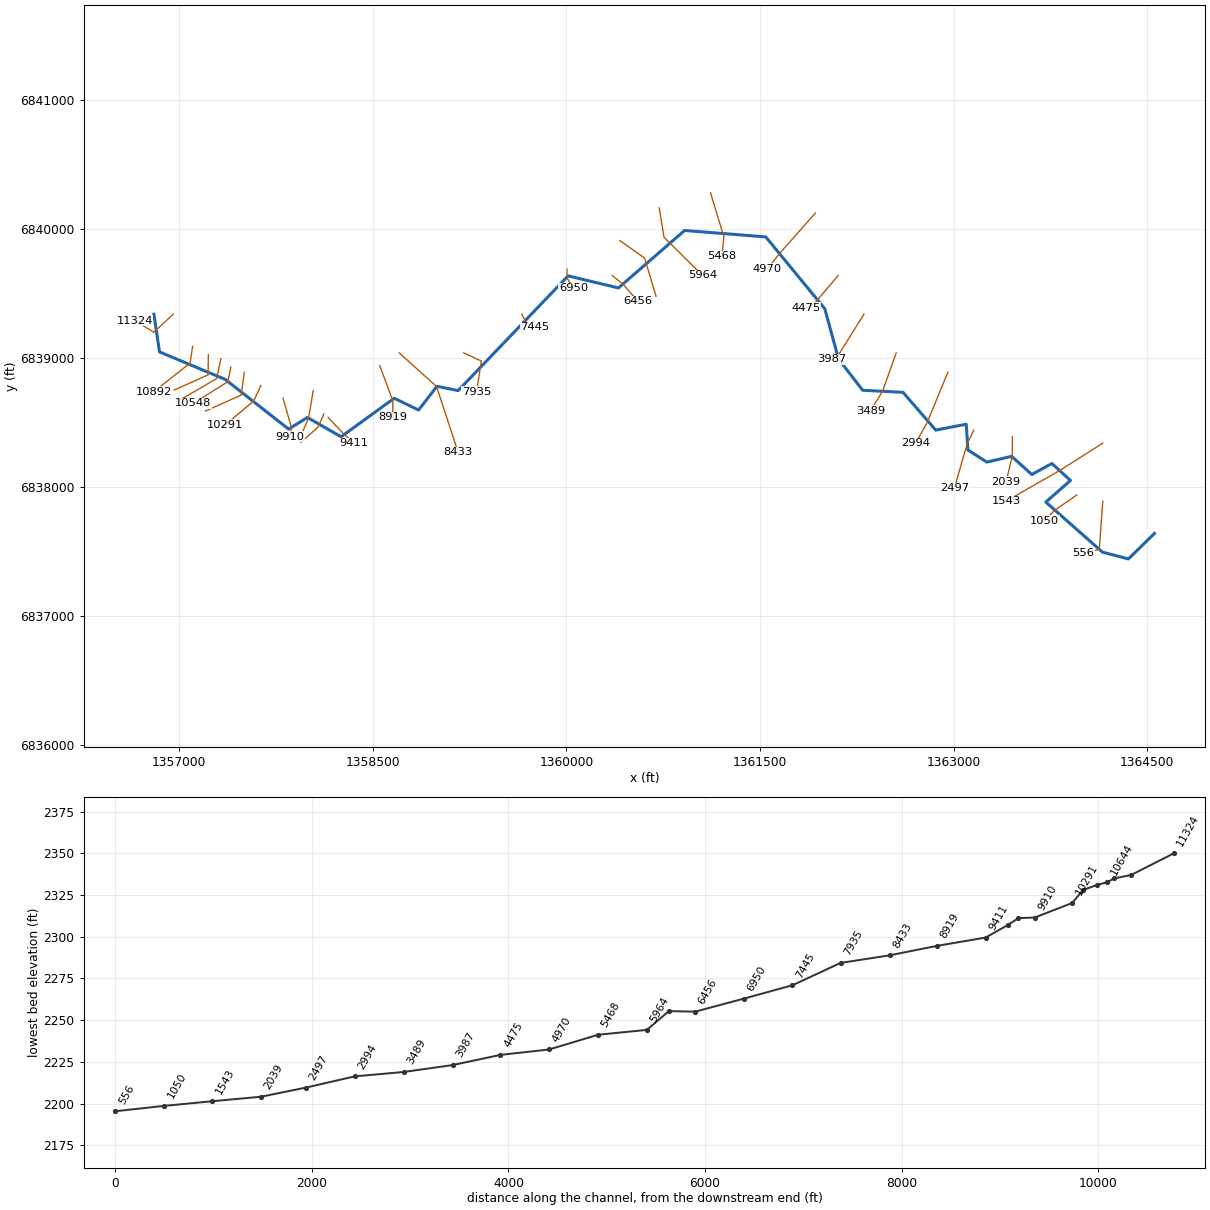
--- Prong Creek.prj (project) ---

Proj Title=Prong Creek Base Level Engineering
Current Plan=p01
Default Exp/Contr=0.3,0.1
English Units
Geom File=g01
Flow File=f01
Plan File=p01
BEGIN DESCRIPTION:
Prong Creek
END DESCRIPTION:

--- Prong Creek.p01 (plan) ---

Plan Title=Multiple Run
Short Identifier=Multiple
Geom File=g01
Flow File=f01
Subcritical Flow
K Sum by GR= 0
Std Step Tol= 0.01
Critical Tol= 0.01
Num of Std Step Trials= 20
Max Error Tol= 0.3
Flow Tol Ratio= 0.001
Split Flow NTrial= 30
Split Flow Tol= 0.02
Split Flow Ratio= 0.02
Log Output Level= 0
Friction Slope Method= 1
Unsteady Friction Slope Method= 2
Unsteady Bridges Friction Slope Method= 1
Parabolic Critical Depth
Global Vel Dist=  1 , 1 , 1
Global Log Level= 0
CheckData=True
Encroach Param= -1, 0, 0, 0
BEGIN DESCRIPTION:
Multiple Run
END DESCRIPTION:

--- Prong Creek.f01 (steady flow) ---

Flow Title=Multiple
Number of Profiles=7
Profile Names=10-year,25-year,50-year,1pct_min,100-year,1pct_plu,500-year
River Rch & RM= Prong Creek,Reach-1,11324
      70      91     108      64     129     256     182
River Rch & RM= Prong Creek,Reach-1,9411
     287     414     523     329     656    1309    1047
River Rch & RM= Prong Creek,Reach-1,2497
     314     455     576     363     724    1445    1160
Boundary for River Rch & Prof#=Prong Creek,Reach-1,1
Up Type=0
Dn Type=3
Dn Slope=0.005
Boundary for River Rch & Prof#=Prong Creek,Reach-1,2
Up Type=0
Dn Type=3
Dn Slope=0.005
Boundary for River Rch & Prof#=Prong Creek,Reach-1,3
Up Type=0
Dn Type=3
Dn Slope=0.005
Boundary for River Rch & Prof#=Prong Creek,Reach-1,4
Up Type=0
Dn Type=3
Dn Slope=0.005
Boundary for River Rch & Prof#=Prong Creek,Reach-1,5
Up Type=0
Dn Type=3
Dn Slope=0.005
Boundary for River Rch & Prof#=Prong Creek,Reach-1,6
Up Type=0
Dn Type=3
Dn Slope=0.005
Boundary for River Rch & Prof#=Prong Creek,Reach-1,7
Up Type=0
Dn Type=3
Dn Slope=0.005

--- Prong Creek.g01 (geometry) ---

Geom Title=Existing Conditions

River Reach=Prong Creek,Reach-1
Reach XY= 30
      1356805.00      6839338.00      1356848.50      6839045.72
      1357357.43      6838832.48      1357848.45      6838447.25
      1357994.36      6838537.44      1358255.00      6838388.00
      1358666.88      6838686.48      1358855.02      6838595.08
      1358997.98      6838778.99      1359161.45      6838745.65
      1360013.28      6839634.94      1360403.50      6839541.46
      1360915.51      6839986.80      1361544.57      6839936.96
      1362001.84      6839379.66      1362108.55      6838989.47
      1362295.18      6838748.46      1362607.54      6838732.30
      1362861.03      6838439.62      1363097.09      6838485.10
      1363110.36      6838285.30      1363256.65      6838191.65
      1363449.20      6838236.12      1363605.06      6838095.29
      1363761.04      6838180.52      1363904.61      6838049.02
      1363713.88      6837881.47      1364152.56      6837493.52
      1364353.58      6837441.04      1364555.00      6837638.00

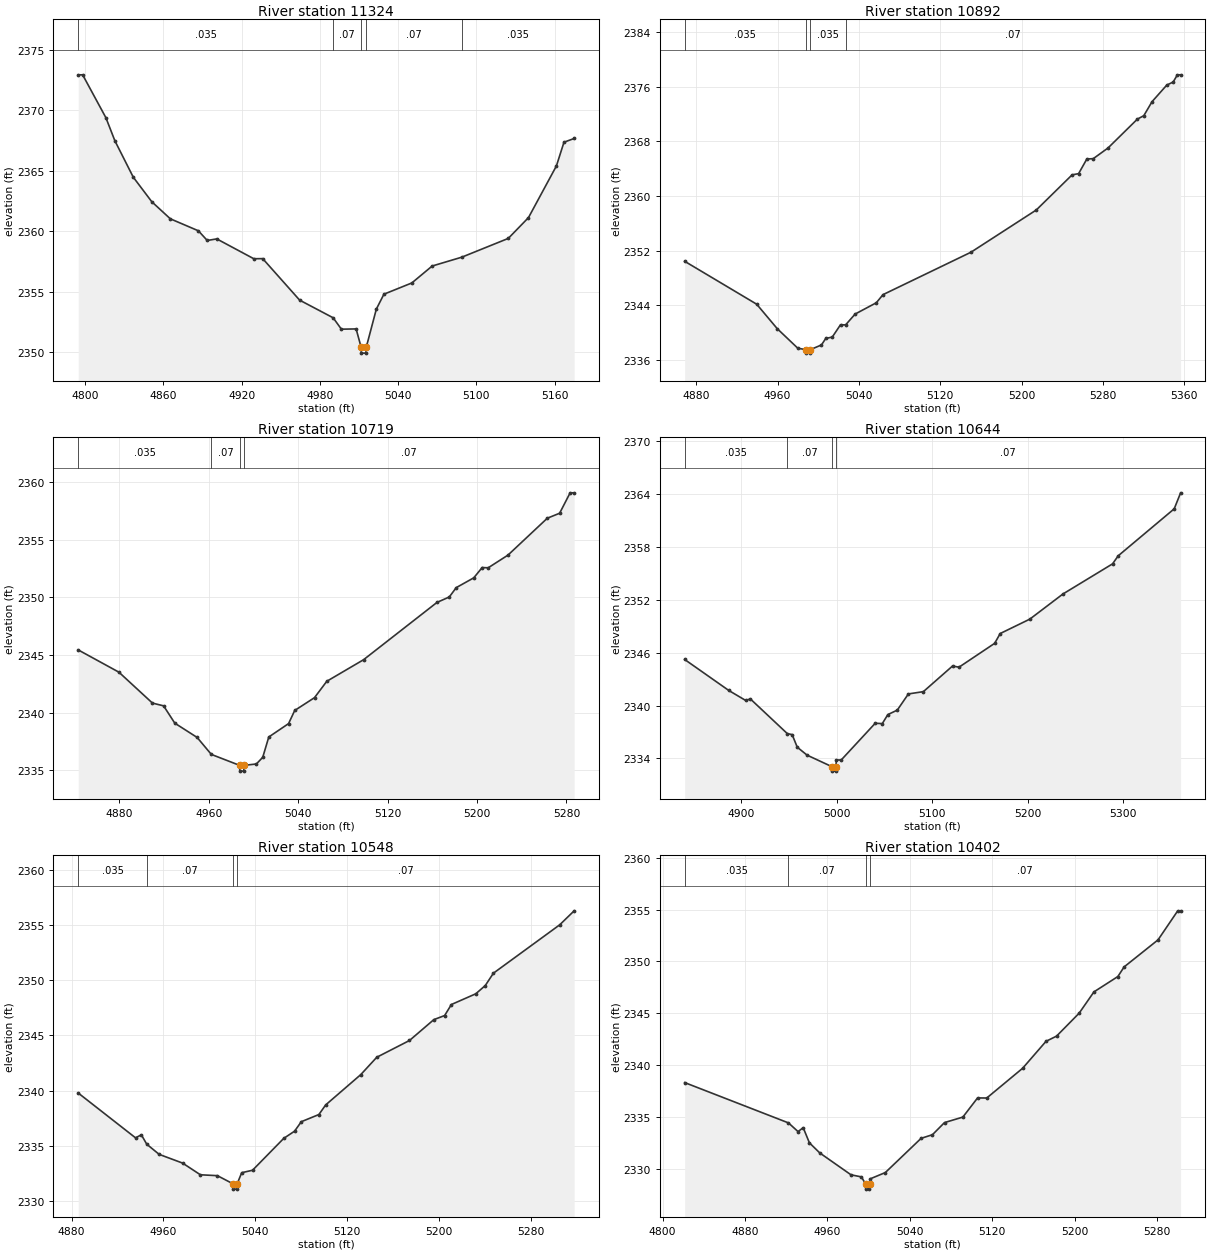
Type RM Length L Ch R = 1,11324,432,432,432
BEGIN DESCRIPTION:
Finn Creek Trib5 22.0
END DESCRIPTION:
XS GIS Cut Line= 3
      1356954.97      6839337.97      1356804.95      6839197.98
      1356655.00      6839288.00
#Sta/Elev= 30
  4794.8 2372.91  4798.2 2372.91  4816.0 2369.37  4822.9 2367.46  4837.0 2364.45
  4851.2 2362.42  4865.4 2361.01  4886.9 2360.02  4893.7 2359.22  4901.0 2359.35
  4929.4 2357.71  4936.2 2357.72  4964.5 2354.29  4990.2 2352.83  4996.5 2351.89
  5007.8 2351.91  5011.6 2350.41  5011.8 2349.91  5015.3 2349.91  5015.6 2350.41
  5023.3 2353.55  5029.1 2354.78  5050.5 2355.71  5066.1 2357.11  5088.8 2357.84
  5124.4 2359.39  5139.9 2361.11  5161.3 2365.38  5167.1 2367.34  5174.9 2367.65
#Mann=5,-1,0
  4794.8   0.035       0  4990.2    0.07       0  5011.6    0.07       0
  5015.6    0.07       0  5088.8   0.035       0
Bank Sta=5011.6,5015.6
Exp/Cntr=0.3,0.1

Type RM Length L Ch R = 1,10892,173,173,173
BEGIN DESCRIPTION:
Finn Creek Trib5 21.0
END DESCRIPTION:
XS GIS Cut Line= 3
      1357104.99      6839087.96      1357085.07      6838958.18
      1356804.97      6838737.98
#Sta/Elev= 30
  4868.7 2350.45  4939.5 2344.17  4959.7 2340.59  4979.9 2337.73  4988.1 2337.51
  4988.3 2337.01  4991.8 2337.01  4992.1 2337.51  5003.2 2338.21  5007.4 2339.16
  5013.8 2339.36  5021.9 2341.16  5026.9 2341.14  5036.3 2342.73  5057.1 2344.38
  5063.7 2345.57  5150.2 2351.78  5214.4 2357.96  5249.6 2363.10  5256.0 2363.28
  5264.1 2365.42  5270.4 2365.47  5284.9 2367.03  5313.8 2371.26  5320.1 2371.76
  5328.2 2373.81  5342.7 2376.24  5349.0 2376.69  5353.1 2377.74  5356.3 2377.74
#Mann=4,-1,0
  4868.7   0.035       0  4988.1   0.035       0  4992.1   0.035       0
  5026.9    0.07       0
Bank Sta=4988.1,4992.1
Exp/Cntr=0.3,0.1

Type RM Length L Ch R = 1,10719,75,75,75
BEGIN DESCRIPTION:
Prong Creek 4063
END DESCRIPTION:
XS GIS Cut Line= 3
      1357226.98      6839024.38      1357224.83      6838867.59
      1356963.11      6838750.07
#Sta/Elev= 30
  4843.2 2345.43  4879.6 2343.50  4909.6 2340.82  4919.6 2340.58  4929.6 2339.08
  4949.6 2337.84  4962.3 2336.37  4987.6 2335.42  4987.8 2334.92  4991.3 2334.92
  4991.6 2335.42  5002.6 2335.54  5008.3 2336.12  5013.7 2337.88  5031.4 2339.04
  5036.9 2340.18  5054.6 2341.29  5065.6 2342.71  5098.5 2344.58  5164.2 2349.55
  5175.2 2350.02  5181.4 2350.83  5197.1 2351.68  5204.6 2352.57  5210.0 2352.55
  5227.7 2353.65  5262.9 2356.85  5273.9 2357.28  5283.3 2359.05  5286.9 2359.05
#Mann=4,-1,0
  4843.2   0.035       0  4962.3    0.07       0  4987.6    0.07       0
  4991.6    0.07       0
Bank Sta=4987.6,4991.6
Exp/Cntr=0.3,0.1

Type RM Length L Ch R = 1,10644,96,96,96
BEGIN DESCRIPTION:
Prong Creek 4065
END DESCRIPTION:
XS GIS Cut Line= 3
      1357324.19      6838993.07      1357289.92      6838837.81
      1356978.51      6838657.19
#Sta/Elev= 30
  4841.0 2345.21  4887.2 2341.70  4904.7 2340.58  4909.8 2340.74  4948.3 2336.83
  4953.5 2336.70  4958.8 2335.28  4969.1 2334.38  4995.2 2333.07  4995.4 2332.57
  4998.9 2332.57  4999.2 2333.07  4999.8 2333.83  5004.8 2333.83  5040.4 2337.99
  5047.8 2337.95  5053.6 2338.97  5063.5 2339.48  5075.1 2341.31  5090.8 2341.57
  5121.3 2344.47  5128.1 2344.34  5165.4 2347.04  5171.2 2348.15  5202.2 2349.78
  5236.9 2352.63  5288.8 2356.04  5294.7 2356.95  5353.3 2362.27  5360.0 2364.08
#Mann=4,-1,0
  4841.0   0.035       0  4948.3    0.07       0  4995.2    0.07       0
  4999.2    0.07       0
Bank Sta=4995.2,4999.2
Exp/Cntr=0.3,0.1

Type RM Length L Ch R = 1,10548,146,146,146
BEGIN DESCRIPTION:
Prong Creek 4064
END DESCRIPTION:
XS GIS Cut Line= 3
      1357400.60      6838927.17      1357378.52      6838815.12
      1357109.44      6838646.22
#Sta/Elev= 30
  4885.8 2339.78  4935.7 2335.72  4940.8 2335.99  4945.5 2335.14  4956.3 2334.22
  4976.7 2333.43  4992.2 2332.37  5007.0 2332.29  5020.3 2331.57  5020.6 2331.07
  5024.1 2331.07  5024.3 2331.57  5028.2 2332.56  5037.6 2332.78  5064.8 2335.67
  5074.2 2336.32  5080.1 2337.18  5095.4 2337.83  5101.3 2338.70  5131.9 2341.45
  5145.8 2343.02  5174.3 2344.54  5195.5 2346.43  5204.9 2346.80  5210.8 2347.80
  5232.0 2348.77  5240.3 2349.52  5247.4 2350.64  5305.1 2355.02  5317.7 2356.29
#Mann=4,-1,0
  4885.8   0.035       0  4945.5    0.07       0  5020.3    0.07       0
  5024.3    0.07       0
Bank Sta=5020.3,5024.3
Exp/Cntr=0.3,0.1

Type RM Length L Ch R = 1,10402,111,111,111
BEGIN DESCRIPTION:
Finn Creek Trib5 20.0
END DESCRIPTION:
XS GIS Cut Line= 3
      1357505.00      6838887.97      1357481.54      6838711.02
      1357204.97      6838587.99
#Sta/Elev= 30
  4821.5 2338.31  4922.2 2334.42  4931.5 2333.58  4936.5 2333.96  4942.5 2332.50
  4952.6 2331.52  4982.9 2329.41  4993.0 2329.21  4997.0 2328.53  4997.2 2328.03
  5000.7 2328.03  5001.0 2328.53  5001.7 2329.03  5016.2 2329.63  5050.9 2332.93
  5061.9 2333.28  5073.6 2334.45  5091.4 2334.98  5105.7 2336.83  5114.6 2336.82
  5149.4 2339.69  5172.1 2342.29  5182.3 2342.79  5204.2 2345.00  5218.6 2347.06
  5241.8 2348.54  5247.9 2349.47  5280.8 2352.08  5299.9 2354.88  5302.7 2354.88
#Mann=4,-1,0
  4821.5   0.035       0  4922.2    0.07       0  4997.0    0.07       0
  5001.0    0.07       0
Bank Sta=4997,5001
Exp/Cntr=0.3,0.1

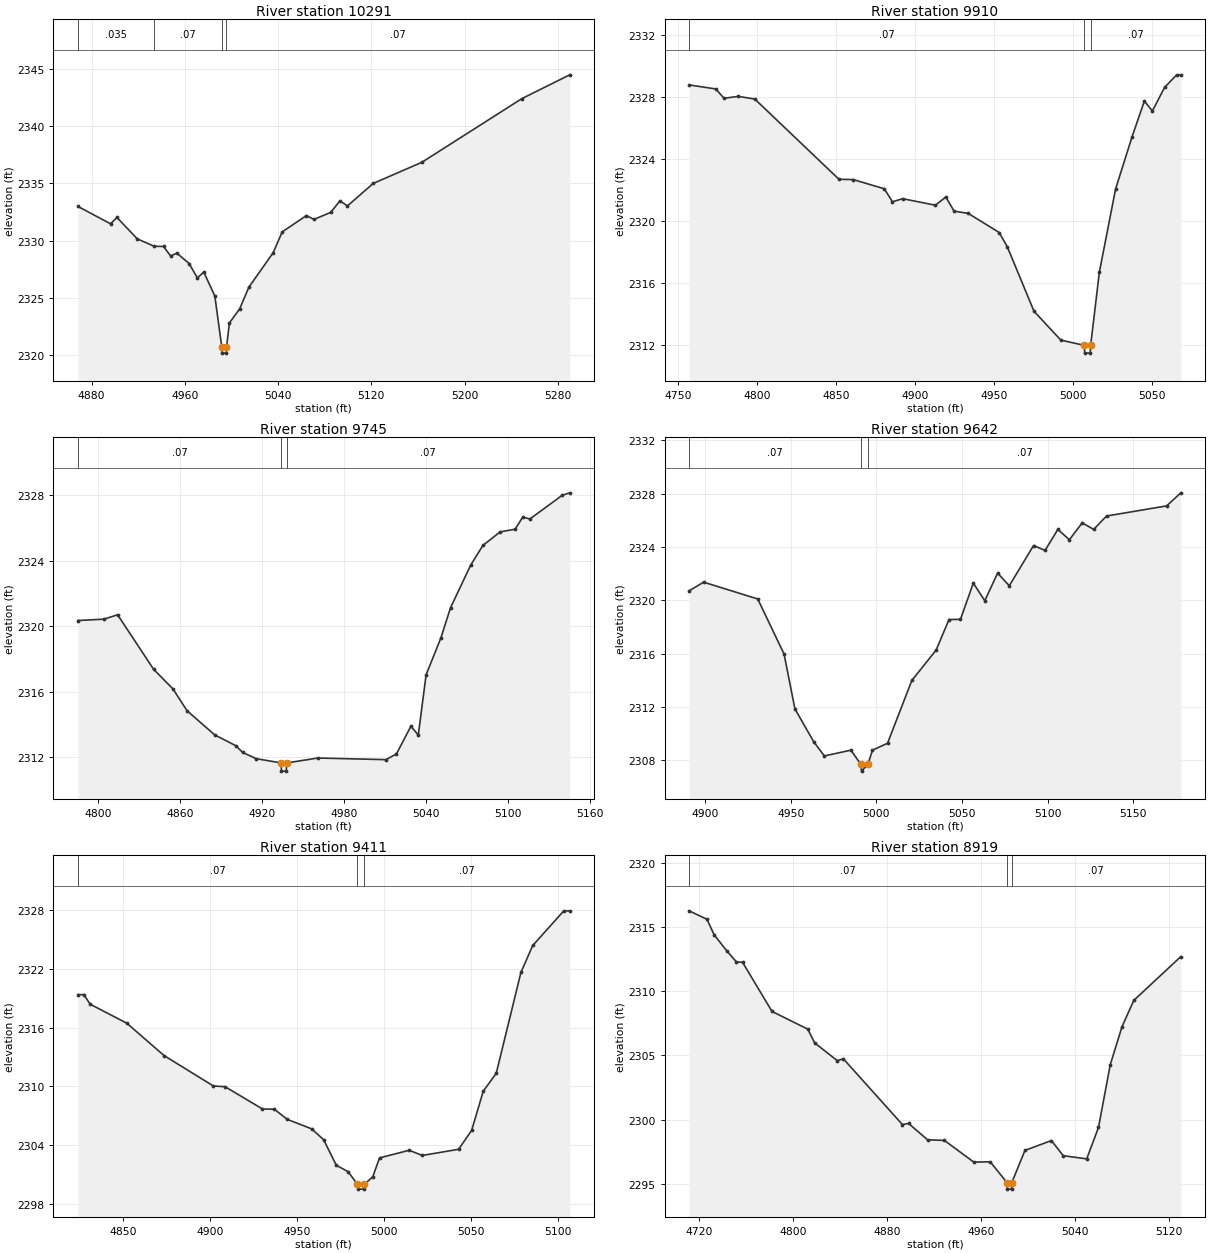
Type RM Length L Ch R = 1,10291,381,381,381
BEGIN DESCRIPTION:
Prong Creek 4062
END DESCRIPTION:
XS GIS Cut Line= 3
      1357633.22      6838784.76      1357578.47      6838664.98
      1357355.49      6838479.25
#Sta/Elev= 30
  4868.3 2332.98  4896.2 2331.47  4901.7 2332.02  4919.2 2330.15  4933.7 2329.51
  4941.7 2329.49  4947.7 2328.67  4953.2 2328.90  4963.7 2328.00  4970.7 2326.75
  4976.2 2327.26  4985.7 2325.17  4991.7 2320.69  4992.0 2320.19  4995.5 2320.19
  4995.7 2320.69  4998.2 2322.82  5007.1 2324.07  5014.9 2325.94  5035.7 2328.94
  5043.5 2330.76  5064.3 2332.19  5070.8 2331.85  5085.2 2332.47  5093.0 2333.47
  5099.5 2333.03  5121.6 2334.99  5163.3 2336.83  5249.2 2342.39  5290.2 2344.46
#Mann=4,-1,0
  4868.3   0.035       0  4933.7    0.07       0  4991.7    0.07       0
  4995.7    0.07       0
Bank Sta=4991.7,4995.7
Exp/Cntr=0.3,0.1

Type RM Length L Ch R = 1,9910,165,165,165
BEGIN DESCRIPTION:
Finn Creek Trib5 19.0
END DESCRIPTION:
XS GIS Cut Line= 3
      1357805.00      6838687.99      1357871.69      6838454.32
      1357855.00      6838387.99
#Sta/Elev= 30
  4757.0 2328.78  4773.9 2328.52  4779.1 2327.92  4788.2 2328.04  4798.6 2327.87
  4851.9 2322.70  4861.0 2322.68  4880.6 2322.09  4885.8 2321.25  4892.2 2321.45
  4913.0 2321.03  4919.6 2321.56  4924.8 2320.65  4933.8 2320.50  4953.4 2319.27
  4958.6 2318.33  4975.4 2314.20  4992.4 2312.34  5007.3 2312.00  5007.5 2311.50
  5011.0 2311.50  5011.3 2312.00  5016.8 2316.71  5027.1 2322.08  5037.5 2325.43
  5045.3 2327.74  5050.4 2327.10  5058.1 2328.62  5065.8 2329.43  5068.4 2329.43
#Mann=3,-1,0
  4757.0    0.07       0  5007.3    0.07       0  5011.3    0.07       0
Bank Sta=5007.3,5011.3
Exp/Cntr=0.3,0.1

Type RM Length L Ch R = 1,9745,103,103,103
BEGIN DESCRIPTION:
Prong Creek 4066
END DESCRIPTION:
XS GIS Cut Line= 3
      1358039.49      6838746.63      1358003.35      6838534.89
      1357946.50      6838401.17
#Sta/Elev= 30
  4785.2 2320.34  4804.1 2320.42  4814.2 2320.69  4840.6 2317.36  4854.8 2316.16
  4865.0 2314.84  4885.3 2313.36  4900.8 2312.70  4905.8 2312.29  4915.7 2311.91
  4934.0 2311.65  4934.2 2311.15  4937.7 2311.15  4938.0 2311.65  4960.9 2311.95
  5010.7 2311.85  5018.4 2312.20  5029.0 2313.89  5034.4 2313.35  5040.1 2317.02
  5051.0 2319.29  5058.0 2321.12  5072.7 2323.71  5081.7 2324.92  5094.4 2325.75
  5105.3 2325.91  5110.8 2326.64  5116.2 2326.54  5139.8 2327.98  5145.3 2328.13
#Mann=3,-1,0
  4785.2    0.07       0  4934.0    0.07       0  4938.0    0.07       0
Bank Sta=4934,4938
Exp/Cntr=0.3,0.1

Type RM Length L Ch R = 1,9642,231,231,231
BEGIN DESCRIPTION:
Prong Creek 4061
END DESCRIPTION:
XS GIS Cut Line= 3
      1358121.67      6838564.76      1358078.20      6838464.36
      1357945.91      6838345.57
#Sta/Elev= 30
  4890.6 2320.72  4899.1 2321.37  4930.7 2320.11  4946.1 2315.97  4952.4 2311.87
  4963.3 2309.42  4969.6 2308.34  4985.1 2308.77  4991.0 2307.70  4991.3 2307.20
  4995.0 2307.70  4997.7 2308.77  5006.5 2309.29  5020.7 2314.00  5034.9 2316.28
  5042.4 2318.57  5049.1 2318.58  5056.6 2321.30  5063.3 2319.98  5070.8 2322.05
  5077.6 2321.10  5091.8 2324.12  5098.5 2323.75  5106.0 2325.33  5112.7 2324.55
  5120.2 2325.82  5126.9 2325.33  5134.4 2326.33  5169.5 2327.09  5177.8 2328.07
#Mann=3,-1,0
  4890.6    0.07       0  4991.0    0.07       0  4995.0    0.07       0
Bank Sta=4991,4995
Exp/Cntr=0.3,0.1

Type RM Length L Ch R = 1,9411,492,492,492
BEGIN DESCRIPTION:
Finn Creek Trib5 18.0
END DESCRIPTION:
XS GIS Cut Line= 3
      1358155.03      6838537.97      1358275.33      6838409.37
      1358355.03      6838337.98
#Sta/Elev= 30
  4823.9 2319.36  4827.3 2319.36  4830.9 2318.38  4852.0 2316.44  4873.4 2313.14
  4901.8 2310.03  4908.6 2309.95  4930.1 2307.68  4937.0 2307.65  4944.3 2306.62
  4958.4 2305.65  4965.3 2304.54  4972.6 2301.93  4979.4 2301.27  4984.8 2299.99
  4985.0 2299.49  4988.5 2299.49  4988.8 2299.99  4993.6 2300.75  4997.5 2302.68
  5014.6 2303.46  5022.1 2302.93  5043.0 2303.56  5050.5 2305.48  5057.2 2309.49
  5064.7 2311.33  5078.9 2321.63  5085.7 2324.38  5103.6 2327.92  5107.0 2327.92
#Mann=3,-1,0
  4823.9    0.07       0  4984.8    0.07       0  4988.8    0.07       0
Bank Sta=4984.8,4988.8
Exp/Cntr=0.3,0.1

Type RM Length L Ch R = 1,8919,486,486,486
BEGIN DESCRIPTION:
Finn Creek Trib5 17.0
END DESCRIPTION:
XS GIS Cut Line= 3
      1358555.00      6838937.99      1358655.41      6838667.85
      1358655.00      6838538.05
#Sta/Elev= 30
  4711.8 2316.28  4727.0 2315.62  4733.1 2314.41  4743.8 2313.16  4752.0 2312.30
  4757.3 2312.26  4782.3 2308.43  4812.7 2307.05  4818.5 2305.98  4837.7 2304.60
  4843.0 2304.73  4893.1 2299.61  4898.4 2299.69  4914.5 2298.42  4928.8 2298.37
  4953.8 2296.68  4967.8 2296.70  4982.1 2295.07  4982.4 2294.57  4985.9 2294.57
  4986.1 2295.07  4997.3 2297.59  5019.8 2298.36  5029.8 2297.18  5049.8 2296.93
  5059.8 2299.38  5069.8 2304.27  5079.8 2307.24  5089.8 2309.29  5129.8 2312.71
#Mann=3,-1,0
  4711.8    0.07       0  4982.1    0.07       0  4986.1    0.07       0
Bank Sta=4982.1,4986.1
Exp/Cntr=0.3,0.1

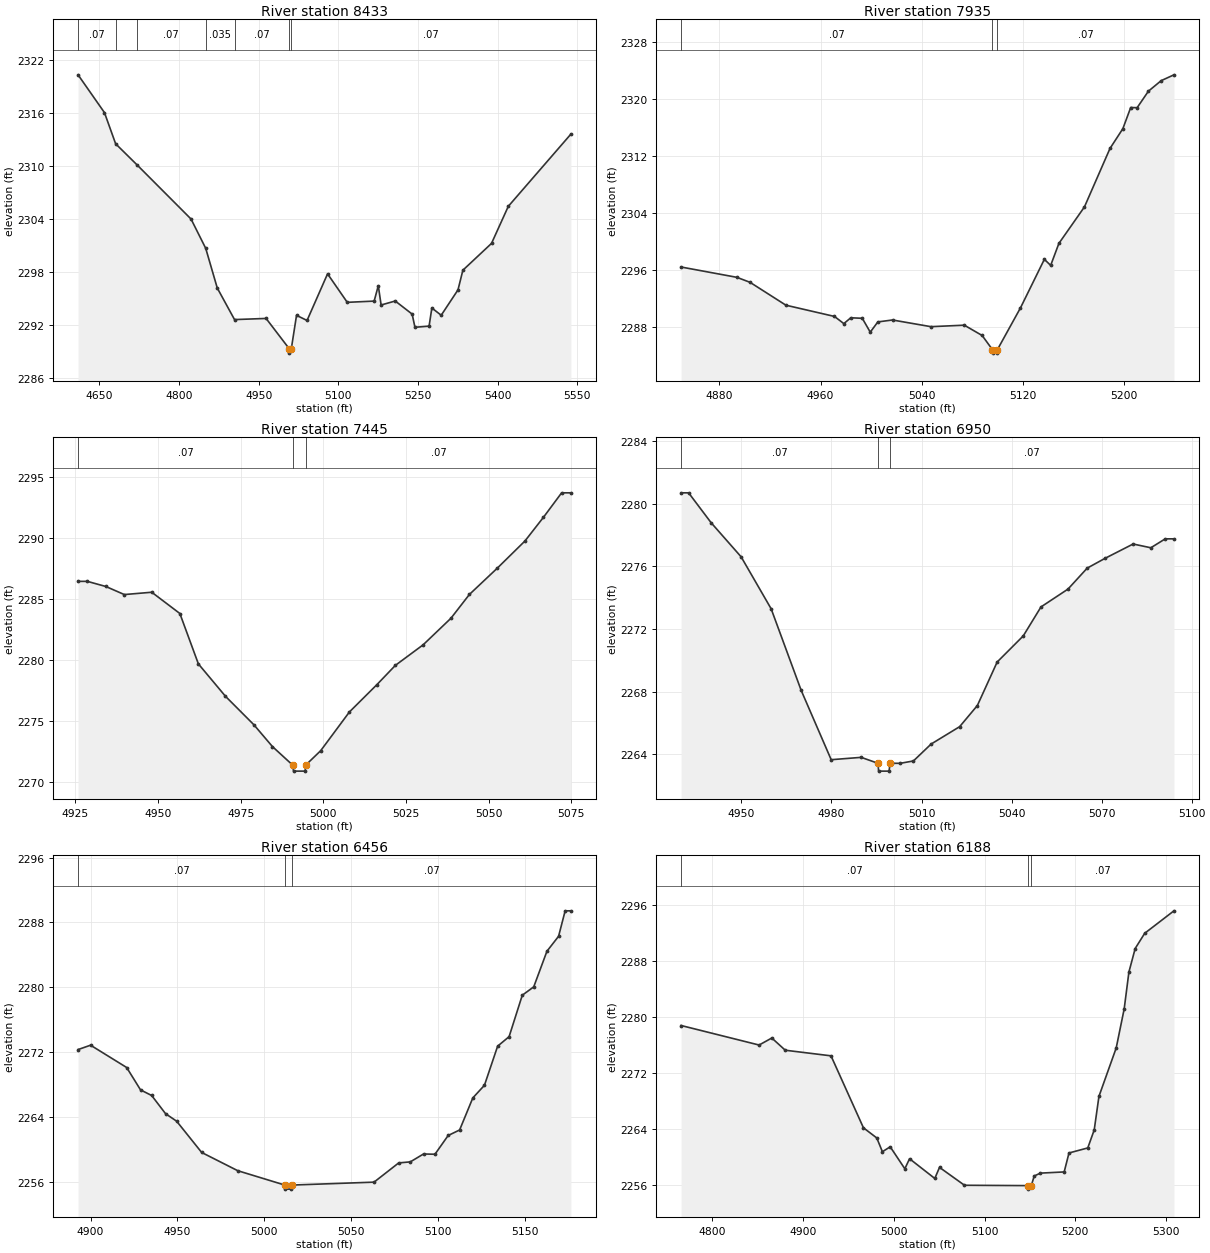
Type RM Length L Ch R = 1,8433,498,498,498
BEGIN DESCRIPTION:
Finn Creek Trib5 16.0
END DESCRIPTION:
XS GIS Cut Line= 3
      1358704.96      6839038.03      1358994.62      6838777.03
      1359162.05      6838266.07
#Sta/Elev= 30
  4610.1 2320.30  4659.8 2316.03  4680.8 2312.51  4720.5 2310.16  4822.8 2304.00
  4850.4 2300.69  4872.1 2296.21  4904.6 2292.64  4964.0 2292.77  5007.5 2289.35
  5007.8 2288.85  5011.5 2289.35  5021.3 2293.12  5041.1 2292.54  5079.7 2297.81
  5116.8 2294.59  5167.4 2294.73  5175.2 2296.47  5180.5 2294.29  5207.1 2294.74
  5238.9 2293.26  5244.2 2291.77  5270.8 2291.90  5276.0 2293.95  5293.6 2293.13
  5325.2 2296.00  5334.4 2298.22  5388.3 2301.25  5419.9 2305.44  5537.7 2313.60
#Mann=7,-1,0
  4610.1    0.07       0  4680.8   0.035       0  4720.5    0.07       0
  4850.4   0.035       0  4904.6    0.07       0  5007.5    0.07       0
  5011.5    0.07       0
Bank Sta=5007.5,5011.5
Exp/Cntr=0.3,0.1

Type RM Length L Ch R = 1,7935,490,490,490
BEGIN DESCRIPTION:
Finn Creek Trib5 15.0
END DESCRIPTION:
XS GIS Cut Line= 3
      1359205.00      6839038.00      1359341.34      6838974.75
      1359305.00      6838738.02
#Sta/Elev= 30
  4849.7 2296.42  4893.8 2294.97  4904.2 2294.27  4932.6 2291.05  4971.0 2289.47
  4978.4 2288.46  4983.9 2289.28  4993.0 2289.21  4999.3 2287.26  5005.3 2288.70
  5016.9 2288.97  5047.3 2288.03  5073.7 2288.24  5087.8 2286.79  5095.9 2284.81
  5096.1 2284.31  5099.6 2284.31  5099.9 2284.81  5118.1 2290.67  5137.0 2297.50
  5142.0 2296.65  5148.5 2299.74  5168.7 2304.87  5188.9 2313.09  5199.1 2315.88
  5205.3 2318.85  5210.4 2318.83  5219.3 2321.15  5229.4 2322.63  5239.5 2323.45
#Mann=3,-1,0
  4849.7    0.07       0  5095.9    0.07       0  5099.9    0.07       0
Bank Sta=5095.9,5099.9
Exp/Cntr=0.3,0.1

Type RM Length L Ch R = 1,7445,495,495,495
BEGIN DESCRIPTION:
Finn Creek Trib5 14.0
END DESCRIPTION:
XS GIS Cut Line= 3
      1359655.01      6839337.97      1359687.96      6839271.49
      1359754.96      6839238.02
#Sta/Elev= 26
  4925.8 2286.45  4928.6 2286.45  4934.2 2286.03  4939.8 2285.37  4948.1 2285.56
  4956.6 2283.82  4962.2 2279.70  4970.4 2277.05  4979.0 2274.72  4984.6 2272.94
  4990.7 2271.43  4991.0 2270.93  4994.5 2270.93  4994.7 2271.43  4999.2 2272.60
  5007.9 2275.77  5016.2 2278.00  5021.8 2279.58  5030.2 2281.26  5038.6 2283.43
  5044.2 2285.38  5052.6 2287.52  5061.0 2289.75  5066.6 2291.69  5072.1 2293.69
  5074.9 2293.69
#Mann=3,-1,0
  4925.8    0.07       0  4990.7    0.07       0  4994.7    0.07       0
Bank Sta=4990.7,4994.7
Exp/Cntr=0.3,0.1

Type RM Length L Ch R = 1,6950,494,494,494
BEGIN DESCRIPTION:
Finn Creek Trib5 13.0
END DESCRIPTION:
XS GIS Cut Line= 3
      1360005.00      6839688.01      1360005.30      6839617.91
      1360055.00      6839538.00
#Sta/Elev= 28
  4929.9 2280.70  4932.4 2280.70  4939.9 2278.79  4949.9 2276.61  4959.9 2273.29
  4969.9 2268.08  4979.9 2263.65  4989.9 2263.80  4995.5 2263.42  4995.7 2262.92
  4999.2 2262.92  4999.5 2263.42  5000.0 2263.42  5002.9 2263.42  5007.3 2263.57
  5013.2 2264.65  5022.7 2265.76  5028.6 2267.11  5035.2 2269.89  5043.9 2271.56
  5049.8 2273.41  5058.8 2274.55  5065.2 2275.89  5071.1 2276.51  5080.5 2277.43
  5086.4 2277.19  5091.2 2277.76  5094.1 2277.76
#Mann=3,-1,0
  4929.9    0.07       0  4995.5    0.07       0  4999.5    0.07       0
Bank Sta=4995.5,4999.5
Exp/Cntr=0.3,0.1

Type RM Length L Ch R = 1,6456,268,268,268
BEGIN DESCRIPTION:
Finn Creek Trib5 12.0
END DESCRIPTION:
XS GIS Cut Line= 3
      1360354.97      6839638.02      1360438.52      6839570.86
      1360555.01      6839437.99
#Sta/Elev= 30
  4892.8 2272.33  4900.0 2272.87  4920.8 2270.12  4928.8 2267.36  4935.2 2266.67
  4943.2 2264.43  4949.6 2263.50  4964.0 2259.65  4984.8 2257.40  5011.9 2255.63
  5012.2 2255.13  5015.7 2255.13  5015.9 2255.63  5063.3 2255.99  5077.5 2258.36
  5084.2 2258.49  5091.8 2259.46  5098.4 2259.43  5106.0 2261.74  5112.6 2262.42
  5120.2 2266.37  5126.9 2267.93  5134.5 2272.75  5141.1 2273.92  5148.7 2279.03
  5155.3 2280.06  5162.9 2284.45  5169.6 2286.29  5173.4 2289.43  5176.7 2289.43
#Mann=3,-1,0
  4892.8    0.07       0  5011.9    0.07       0  5015.9    0.07       0
Bank Sta=5011.9,5015.9
Exp/Cntr=0.3,0.1

Type RM Length L Ch R = 1,6188,224,224,224
BEGIN DESCRIPTION:
Finn Creek Trib5 11.1
END DESCRIPTION:
XS GIS Cut Line= 3
      1360414.98      6839908.33      1360605.87      6839772.64
      1360694.77      6839477.12
#Sta/Elev= 30
  4765.8 2278.76  4851.7 2275.98  4865.7 2276.98  4880.5 2275.24  4930.9 2274.44
  4966.6 2264.19  4981.3 2262.74  4987.5 2260.78  4996.1 2261.48  5012.2 2258.35
  5017.4 2259.78  5045.2 2256.97  5050.4 2258.55  5077.9 2256.00  5147.5 2255.95
  5147.7 2255.45  5151.5 2255.95  5154.7 2257.32  5161.5 2257.73  5187.7 2257.90
  5193.0 2260.60  5213.7 2261.32  5220.8 2263.89  5226.0 2268.67  5245.0 2275.56
  5253.8 2281.13  5259.0 2286.38  5265.9 2289.73  5276.4 2291.90  5308.6 2295.10
#Mann=3,-1,0
  4765.8    0.07       0  5147.5    0.07       0  5151.5    0.07       0
Bank Sta=5147.5,5151.5
Exp/Cntr=0.3,0.1

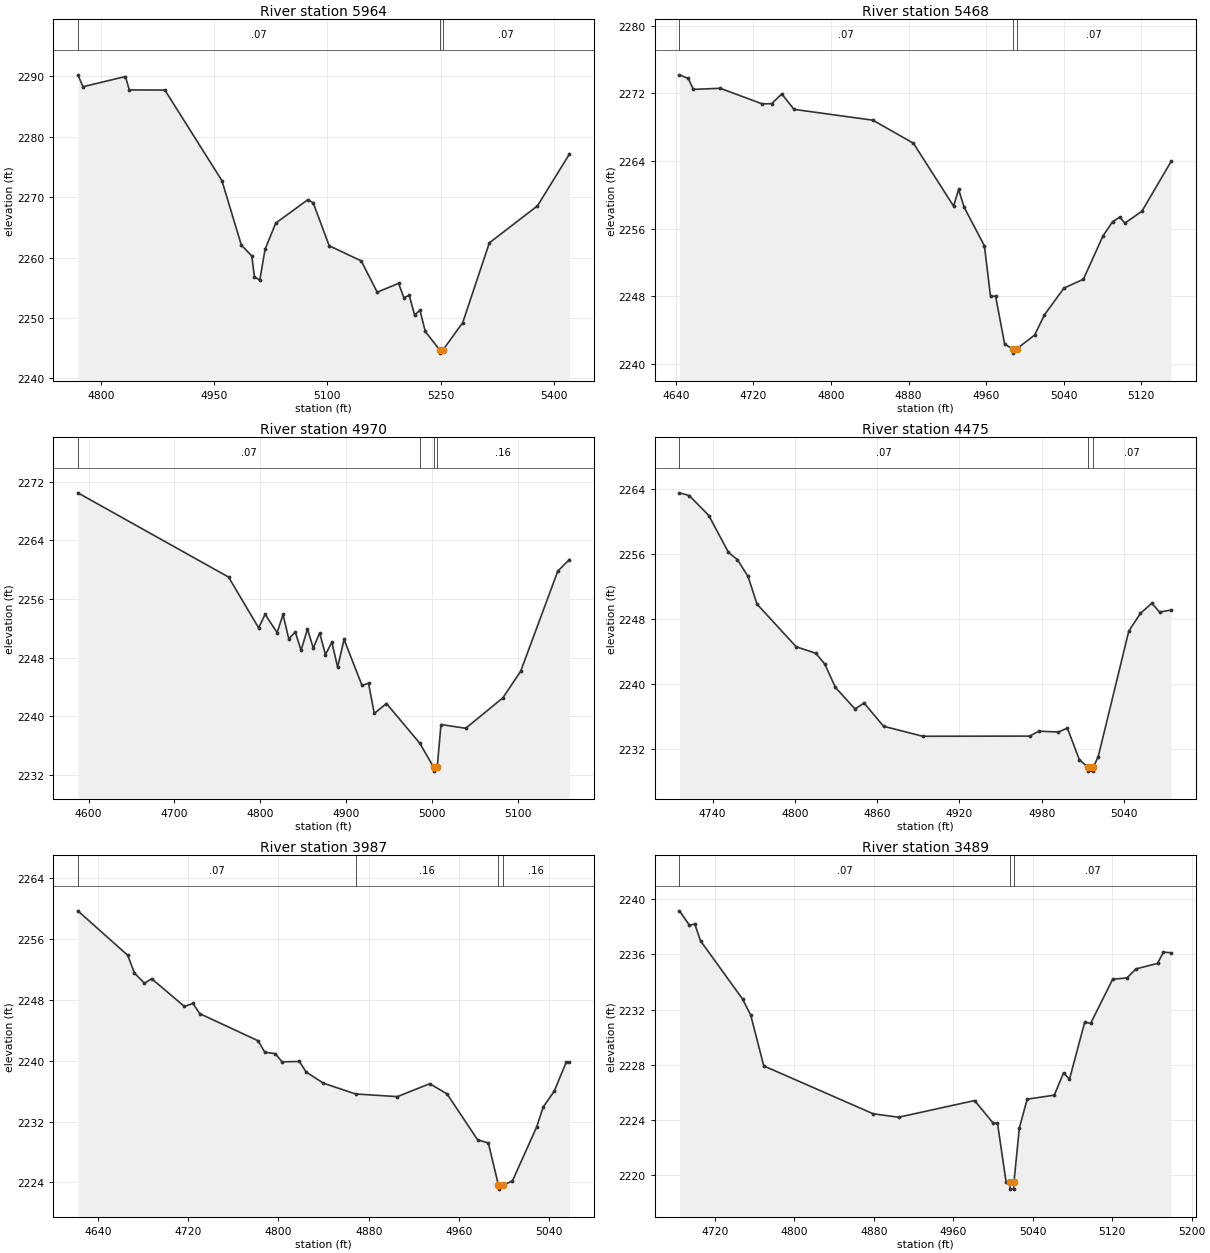
Type RM Length L Ch R = 1,5964,496,496,496
BEGIN DESCRIPTION:
Finn Creek Trib5 11.0
END DESCRIPTION:
XS GIS Cut Line= 3
      1360719.23      6840161.65      1360756.50      6839934.39
      1361055.03      6839637.97
#Sta/Elev= 30
  4769.7 2290.27  4776.5 2288.30  4832.7 2289.99  4837.8 2287.77  4884.9 2287.75
  4960.4 2272.77  4986.2 2262.08  5000.0 2260.29  5003.5 2256.85  5010.6 2256.29
  5017.6 2261.39  5031.7 2265.72  5074.2 2269.60  5081.3 2269.08  5102.5 2261.98
  5144.9 2259.47  5166.1 2254.29  5194.4 2255.75  5201.4 2253.38  5208.5 2253.77
  5215.6 2250.50  5222.7 2251.32  5229.7 2247.80  5249.0 2244.70  5249.2 2244.20
  5253.0 2244.70  5279.3 2249.24  5314.6 2262.46  5378.3 2268.58  5420.7 2277.17
#Mann=3,-1,0
  4769.7    0.07       0  5249.0    0.07       0  5253.0    0.07       0
Bank Sta=5249,5253
Exp/Cntr=0.3,0.1

Type RM Length L Ch R = 1,5468,498,498,498
BEGIN DESCRIPTION:
Finn Creek Trib5 10.0
END DESCRIPTION:
XS GIS Cut Line= 3
      1361116.53      6840278.91      1361219.98      6839937.96
      1361205.00      6839788.01
#Sta/Elev= 30
  4643.7 2274.18  4652.8 2273.75  4658.0 2272.46  4685.7 2272.59  4729.0 2270.75
  4738.7 2270.77  4749.2 2271.92  4761.9 2270.10  4843.2 2268.82  4885.0 2266.10
  4926.4 2258.67  4931.6 2260.64  4937.3 2258.53  4958.2 2253.98  4964.5 2248.00
  4969.7 2248.04  4979.1 2242.36  4987.5 2241.80  4987.8 2241.30  4991.5 2241.80
  5010.0 2243.44  5020.1 2245.82  5040.2 2248.98  5060.3 2250.03  5080.4 2255.13
  5090.4 2256.83  5097.9 2257.37  5103.0 2256.66  5120.6 2258.06  5150.7 2263.94
#Mann=3,-1,0
  4643.7    0.07       0  4987.5    0.07       0  4991.5    0.07       0
Bank Sta=4987.5,4991.5
Exp/Cntr=0.3,0.1

Type RM Length L Ch R = 1,4970,495,495,495
BEGIN DESCRIPTION:
Finn Creek Trib5 9.0
END DESCRIPTION:
XS GIS Cut Line= 3
      1361928.75      6840121.69      1361655.09      6839813.04
      1361554.98      6839687.97
#Sta/Elev= 30
  4587.5 2270.51  4763.0 2259.00  4798.1 2252.05  4805.6 2253.91  4819.6 2251.40
  4826.5 2253.88  4833.2 2250.56  4840.8 2251.49  4847.5 2248.98  4855.0 2251.91
  4861.7 2249.29  4869.2 2251.36  4875.9 2248.40  4883.4 2250.09  4890.1 2246.67
  4897.6 2250.47  4918.5 2244.19  4926.1 2244.48  4932.8 2240.36  4947.0 2241.71
  4985.9 2236.27  5002.1 2232.97  5002.3 2232.47  5006.1 2232.97  5010.5 2238.84
  5039.3 2238.33  5082.5 2242.48  5103.3 2246.11  5146.6 2259.82  5160.2 2261.39
#Mann=4,-1,0
  4587.5    0.07       0  4985.9    0.16       0  5002.1    0.07       0
  5006.1    0.16       0
Bank Sta=5002.1,5006.1
Exp/Cntr=0.3,0.1

Type RM Length L Ch R = 1,4475,488,488,488
BEGIN DESCRIPTION:
Finn Creek Trib5 8.0
END DESCRIPTION:
XS GIS Cut Line= 3
      1362104.98      6839637.98      1361921.60      6839421.00
      1361855.02      6839388.01
#Sta/Elev= 30
  4715.9 2263.48  4723.0 2263.15  4737.3 2260.69  4751.6 2256.16  4758.2 2255.25
  4765.9 2253.20  4772.4 2249.80  4801.0 2244.54  4815.3 2243.74  4821.9 2242.40
  4829.6 2239.54  4843.9 2236.89  4850.5 2237.62  4864.7 2234.76  4893.3 2233.53
  4971.3 2233.55  4977.9 2234.16  4992.2 2234.05  4998.7 2234.54  5007.4 2230.66
  5013.5 2229.74  5013.7 2229.24  5017.2 2229.24  5017.5 2229.74  5021.1 2230.96
  5043.5 2246.48  5052.0 2248.66  5060.3 2249.90  5065.9 2248.81  5074.3 2249.06
#Mann=3,-1,0
  4715.9    0.07       0  5013.5    0.07       0  5017.5    0.07       0
Bank Sta=5013.5,5017.5
Exp/Cntr=0.3,0.1

Type RM Length L Ch R = 1,3987,498,498,498
BEGIN DESCRIPTION:
Finn Creek Trib5 7.0
END DESCRIPTION:
XS GIS Cut Line= 3
      1362304.99      6839337.99      1362104.60      6839017.84
      1362054.99      6838987.99
#Sta/Elev= 30
  4622.3 2259.70  4666.5 2253.85  4672.4 2251.53  4681.3 2250.18  4687.7 2250.78
  4716.7 2247.13  4724.3 2247.53  4730.2 2246.19  4782.0 2242.62  4787.9 2241.12
  4797.3 2240.92  4803.2 2239.85  4818.6 2239.90  4824.5 2238.52  4839.8 2237.05
  4868.3 2235.63  4905.4 2235.28  4934.1 2236.98  4949.4 2235.64  4976.5 2229.60
  4986.0 2229.19  4995.0 2223.62  4995.2 2223.12  4999.0 2223.62  5007.4 2224.22
  5028.7 2231.25  5034.6 2233.91  5044.3 2235.97  5055.0 2239.80  5057.9 2239.80
#Mann=4,-1,0
  4622.3    0.07       0  4868.3    0.16       0  4995.0    0.07       0
  4999.0    0.16       0
Bank Sta=4995,4999
Exp/Cntr=0.3,0.1

Type RM Length L Ch R = 1,3489,495,495,495
BEGIN DESCRIPTION:
Finn Creek Trib5 6.0
END DESCRIPTION:
XS GIS Cut Line= 3
      1362554.99      6839037.98      1362449.14      6838740.45
      1362354.99      6838587.98
#Sta/Elev= 30
  4684.2 2239.16  4694.3 2238.11  4699.6 2238.21  4705.4 2236.99  4747.9 2232.75
  4756.0 2231.59  4769.1 2227.92  4879.3 2224.45  4904.8 2224.20  4981.4 2225.41
  5000.0 2223.78  5004.4 2223.78  5013.1 2219.51  5017.0 2219.49  5017.2 2218.99
  5020.7 2218.99  5021.0 2219.49  5026.4 2223.41  5034.3 2225.51  5061.6 2225.80
  5071.0 2227.43  5076.9 2226.95  5092.3 2231.10  5098.2 2231.00  5120.4 2234.20
  5134.8 2234.30  5143.9 2234.95  5165.6 2235.35  5171.5 2236.17  5179.2 2236.12
#Mann=3,-1,0
  4684.2    0.07       0  5017.0    0.07       0  5021.0    0.07       0
Bank Sta=5017,5021
Exp/Cntr=0.3,0.1

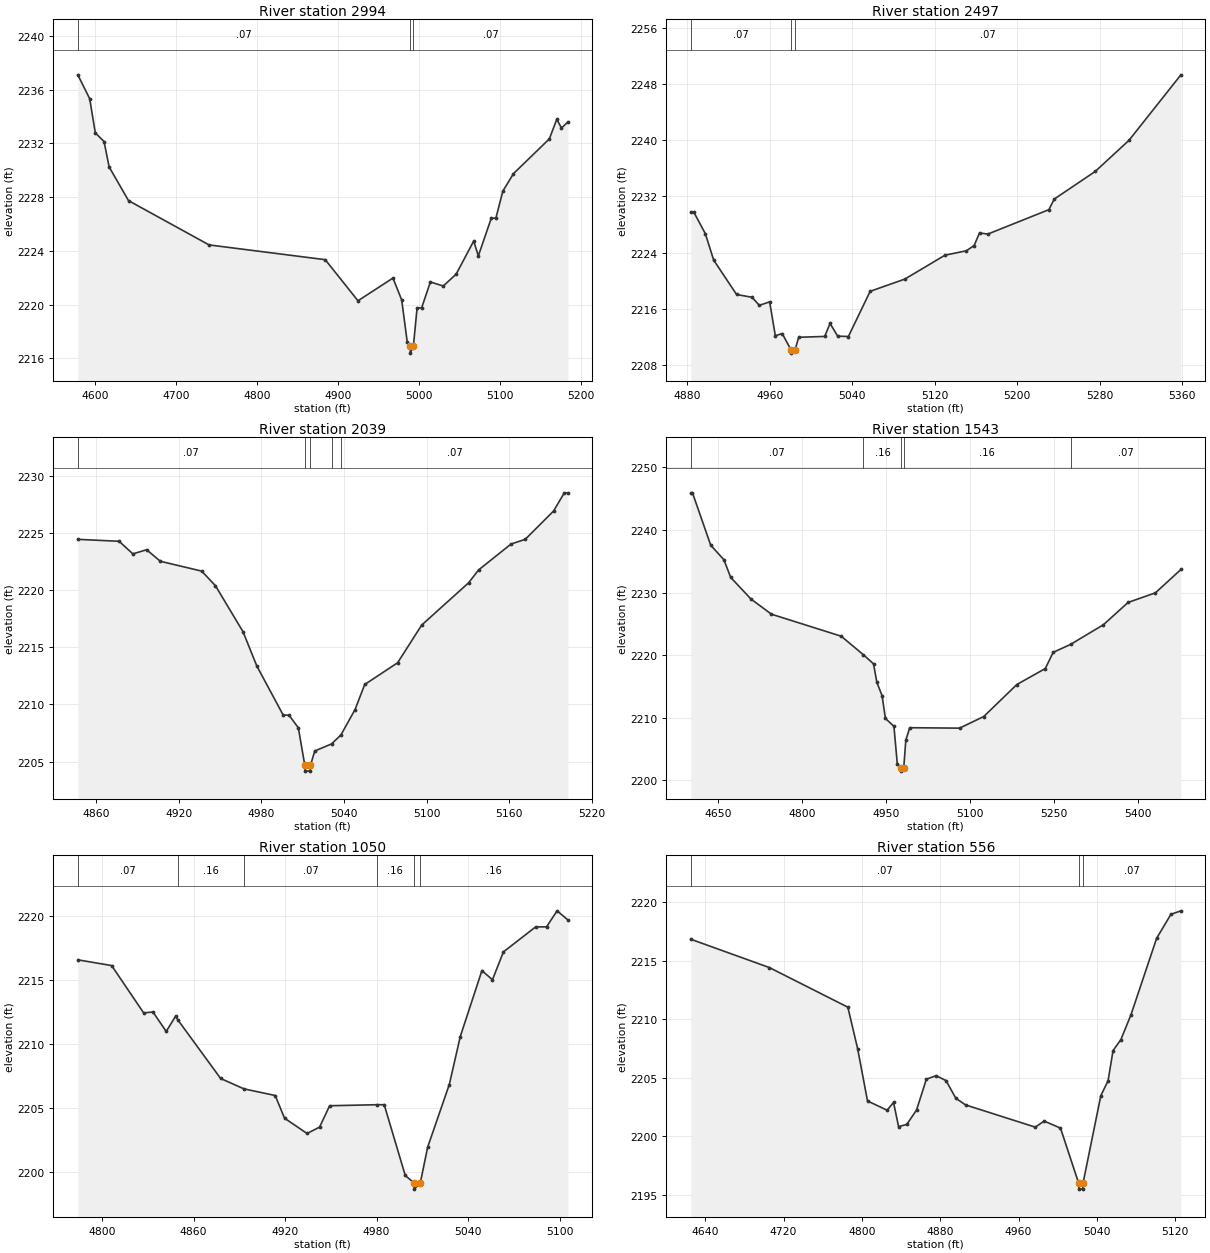
Type RM Length L Ch R = 1,2994,497,497,497
BEGIN DESCRIPTION:
Finn Creek Trib5 5.0
END DESCRIPTION:
XS GIS Cut Line= 3
      1362954.99      6838887.99      1362794.95      6838497.84
      1362705.00      6838338.01
#Sta/Elev= 30
  4578.3 2237.11  4593.0 2235.33  4599.9 2232.79  4610.7 2232.14  4617.0 2230.25
  4640.9 2227.74  4740.4 2224.44  4883.8 2223.34  4924.2 2220.28  4967.4 2221.97
  4978.2 2220.34  4985.1 2217.18  4988.6 2216.88  4988.8 2216.38  4992.6 2216.88
  4997.2 2219.75  5002.8 2219.75  5013.6 2221.68  5029.5 2221.38  5045.4 2222.26
  5067.1 2224.73  5072.8 2223.62  5088.8 2226.43  5094.5 2226.44  5103.1 2228.45
  5116.2 2229.75  5160.5 2232.34  5169.7 2233.80  5175.4 2233.15  5183.4 2233.59
#Mann=3,-1,0
  4578.3    0.07       0  4988.6    0.07       0  4992.6    0.07       0
Bank Sta=4988.6,4992.6
Exp/Cntr=0.3,0.1

Type RM Length L Ch R = 1,2497,458,458,458
BEGIN DESCRIPTION:
Finn Creek Trib5 4.0
END DESCRIPTION:
XS GIS Cut Line= 3
      1363155.00      6838437.99      1363104.52      6838332.77
      1363005.01      6837988.05
#Sta/Elev= 30
  4883.3 2229.79  4886.1 2229.79  4897.4 2226.69  4905.5 2222.92  4927.7 2218.02
  4942.7 2217.62  4949.8 2216.47  4959.8 2216.97  4965.3 2212.15  4972.0 2212.44
  4980.4 2210.16  4980.6 2209.66  4984.5 2210.16  4988.0 2211.92  5013.2 2212.04
  5018.4 2213.89  5025.8 2212.08  5036.2 2212.03  5057.3 2218.47  5090.9 2220.21
  5129.9 2223.62  5150.7 2224.25  5158.2 2225.00  5163.4 2226.79  5171.5 2226.63
  5230.7 2230.11  5235.9 2231.62  5275.6 2235.55  5308.4 2239.99  5358.8 2249.33
#Mann=3,-1,0
  4883.3    0.07       0  4980.4    0.07       0  4984.5    0.07       0
Bank Sta=4980.4,4984.5
Exp/Cntr=0.3,0.1

Type RM Length L Ch R = 1,2039,496,496,496
BEGIN DESCRIPTION:
Finn Creek Trib5 3.0
END DESCRIPTION:
XS GIS Cut Line= 3
      1363455.00      6838388.02      1363453.64      6838234.62
      1363404.99      6838037.95
#Sta/Elev= 30
  4846.6 2224.45  4876.6 2224.28  4886.6 2223.18  4896.6 2223.54  4906.6 2222.53
  4936.6 2221.67  4946.6 2220.39  4966.6 2216.37  4976.6 2213.38  4995.8 2209.07
  5000.0 2209.07  5006.8 2207.96  5011.5 2204.67  5011.8 2204.17  5015.4 2204.17
  5015.6 2204.67  5018.7 2205.93  5030.9 2206.55  5037.7 2207.33  5048.0 2209.56
  5055.0 2211.75  5078.9 2213.65  5096.4 2216.95  5130.4 2220.64  5137.8 2221.78
  5161.3 2224.04  5171.6 2224.45  5192.2 2226.93  5200.0 2228.52  5202.6 2228.52
#Mann=5,-1,0
  4846.6    0.07       0  5011.5    0.07       0  5015.6    0.07       0
  5030.9    0.16       0  5037.7    0.07       0
Bank Sta=5011.5,5015.6
Exp/Cntr=0.3,0.1

Type RM Length L Ch R = 1,1543,493,493,493
BEGIN DESCRIPTION:
Finn Creek Trib5 2.0
END DESCRIPTION:
XS GIS Cut Line= 3
      1364155.01      6838338.01      1363818.31      6838124.48
      1363404.98      6837887.99
#Sta/Elev= 30
  4601.3 2245.95  4604.3 2245.95  4636.8 2237.59  4660.5 2235.24  4672.5 2232.43
  4708.9 2228.96  4745.3 2226.55  4869.9 2223.03  4909.5 2220.06  4927.5 2218.62
  4933.4 2215.67  4942.8 2213.52  4948.7 2209.89  4963.9 2208.63  4969.9 2202.65
  4977.1 2201.97  4977.4 2201.47  4981.4 2201.97  4985.1 2206.40  4992.1 2208.41
  5081.1 2208.34  5124.3 2210.20  5183.3 2215.31  5234.2 2217.87  5248.1 2220.45
  5279.4 2221.73  5337.9 2224.87  5381.9 2228.43  5430.8 2229.97  5476.2 2233.70
#Mann=5,-1,0
  4601.3    0.07       0  4909.5    0.16       0  4977.1    0.07       0
  4981.4    0.16       0  5279.4    0.07       0
Bank Sta=4977.1,4981.4
Exp/Cntr=0.3,0.1

Type RM Length L Ch R = 1,1050,494,494,494
BEGIN DESCRIPTION:
Finn Creek Trib5 1.0
END DESCRIPTION:
XS GIS Cut Line= 3
      1363954.99      6837937.99      1363778.00      6837814.18
      1363705.01      6837738.01
#Sta/Elev= 30
  4784.0 2216.60  4806.2 2216.15  4827.2 2212.45  4833.3 2212.52  4842.0 2211.00
  4848.1 2212.18  4849.9 2211.86  4877.7 2207.32  4893.0 2206.51  4913.5 2205.99
  4919.6 2204.22  4934.4 2203.02  4942.6 2203.52  4949.2 2205.19  4980.2 2205.27
  4985.0 2205.27  4998.8 2199.74  5004.4 2199.17  5004.7 2198.67  5008.7 2199.17
  5013.5 2201.95  5027.7 2206.85  5034.9 2210.60  5049.1 2215.76  5056.0 2215.04
  5063.2 2217.22  5084.3 2219.17  5091.5 2219.18  5098.4 2220.43  5105.5 2219.72
#Mann=6,-1,0
  4784.0    0.07       0  4849.9    0.16       0  4893.0    0.07       0
  4980.2    0.16       0  5004.4    0.07       0  5008.7    0.16       0
Bank Sta=5004.4,5008.7
Exp/Cntr=0.3,0.1

Type RM Length L Ch R = 1,556,0,0,0
BEGIN DESCRIPTION:
Finn Creek Trib5 0.1
END DESCRIPTION:
XS GIS Cut Line= 3
      1364155.00      6837887.99      1364128.07      6837514.15
      1364005.02      6837488.00
#Sta/Elev= 30
  4625.2 2216.85  4705.4 2214.43  4785.6 2211.04  4795.6 2207.49  4805.7 2203.02
  4825.7 2202.23  4832.3 2202.89  4837.4 2200.83  4845.8 2201.01  4855.8 2202.25
  4865.8 2204.88  4875.8 2205.18  4885.9 2204.76  4895.9 2203.25  4905.9 2202.68
  4977.1 2200.78  4986.1 2201.30  5002.8 2200.70  5021.4 2195.98  5021.7 2195.48
  5025.5 2195.48  5025.8 2195.98  5044.0 2203.47  5051.4 2204.75  5056.5 2207.33
  5064.5 2208.27  5074.7 2210.37  5101.0 2216.93  5115.6 2218.98  5125.8 2219.28
#Mann=3,-1,0
  4625.2    0.07       0  5021.4    0.07       0  5025.8    0.07       0
Bank Sta=5021.4,5025.8
Exp/Cntr=0.3,0.1

Chan Stop Cuts=-1