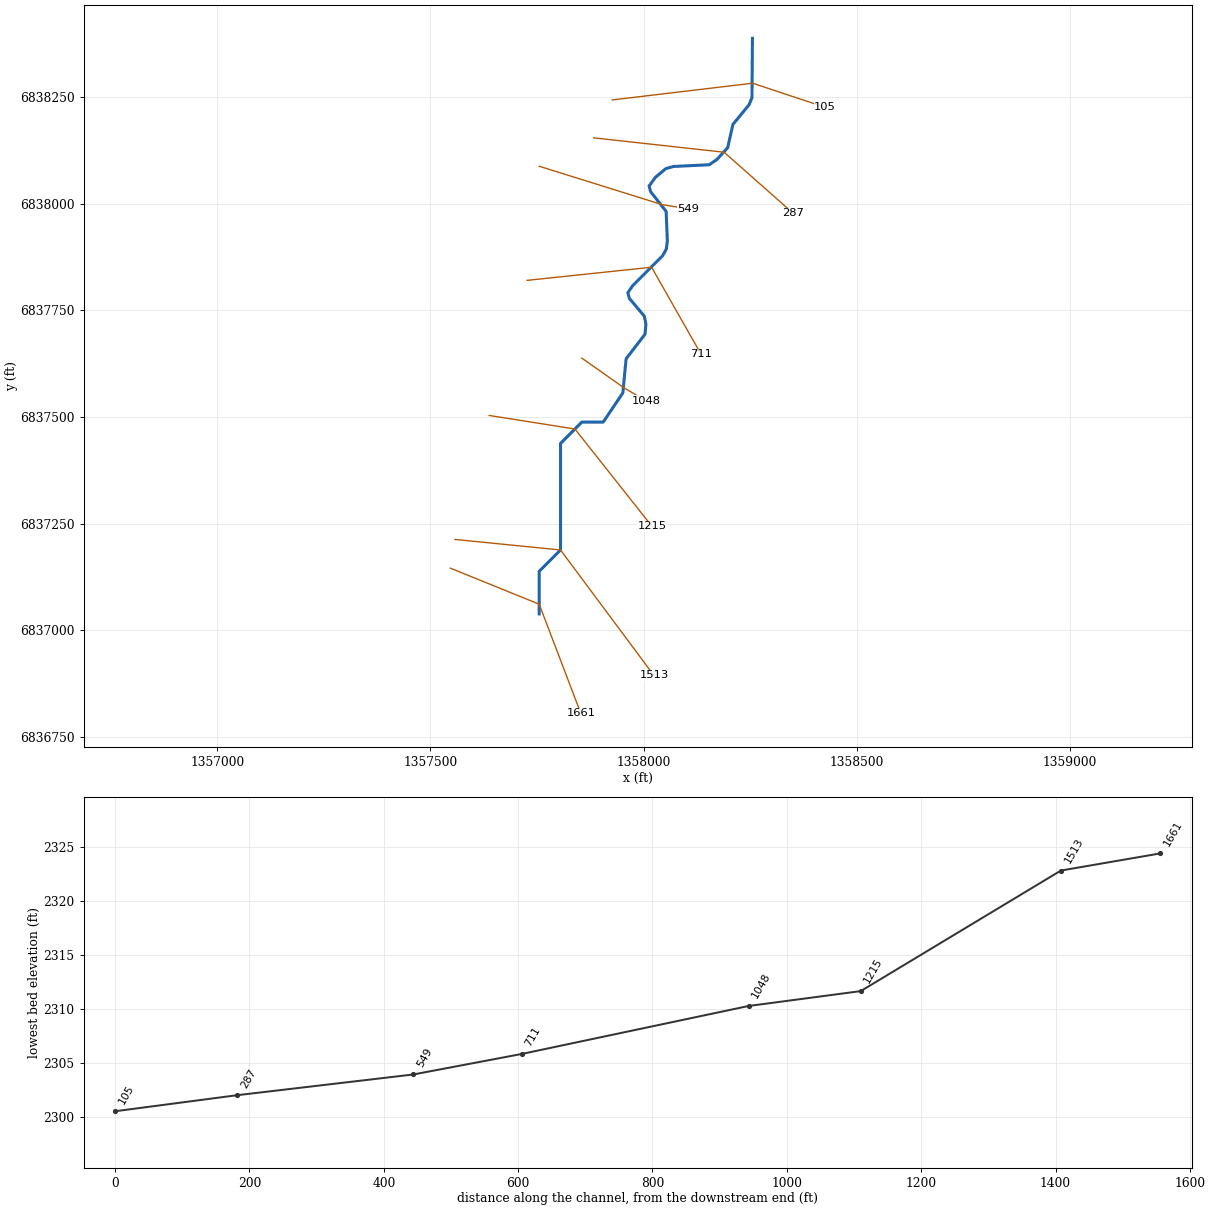
--- Prong Creek Trib1.prj (project) ---

Proj Title=Prong Creek Trib1 Base Level Engineering
Current Plan=p01
Default Exp/Contr=0.3,0.1
English Units
Geom File=g01
Flow File=f01
Plan File=p01
BEGIN DESCRIPTION:
Prong Creek Trib1
END DESCRIPTION:

--- Prong Creek Trib1.p01 (plan) ---

Plan Title=Multiple Run
Short Identifier=Multiple
Geom File=g01
Flow File=f01
Subcritical Flow
K Sum by GR= 0
Std Step Tol= 0.01
Critical Tol= 0.01
Num of Std Step Trials= 20
Max Error Tol= 0.3
Flow Tol Ratio= 0.001
Split Flow NTrial= 30
Split Flow Tol= 0.02
Split Flow Ratio= 0.02
Log Output Level= 0
Friction Slope Method= 1
Unsteady Friction Slope Method= 2
Unsteady Bridges Friction Slope Method= 1
Parabolic Critical Depth
Global Vel Dist=  1 , 1 , 1
Global Log Level= 0
CheckData=True
Encroach Param= -1, 0, 0, 0
BEGIN DESCRIPTION:
Multiple Run
END DESCRIPTION:

--- Prong Creek Trib1.f01 (steady flow) ---

Flow Title=Multiple
Number of Profiles=7
Profile Names=10-year,25-year,50-year,1pct_min,100-year,1pct_plu,500-year
River Rch & RM= Prong Creek Trib,Reach-1,1661
     108     147     178     108     215     429     318
Boundary for River Rch & Prof#=Prong Creek Trib,Reach-1,1
Up Type=0
Dn Type=3
Dn Slope=0.005
Boundary for River Rch & Prof#=Prong Creek Trib,Reach-1,2
Up Type=0
Dn Type=3
Dn Slope=0.005
Boundary for River Rch & Prof#=Prong Creek Trib,Reach-1,3
Up Type=0
Dn Type=3
Dn Slope=0.005
Boundary for River Rch & Prof#=Prong Creek Trib,Reach-1,4
Up Type=0
Dn Type=3
Dn Slope=0.005
Boundary for River Rch & Prof#=Prong Creek Trib,Reach-1,5
Up Type=0
Dn Type=3
Dn Slope=0.005
Boundary for River Rch & Prof#=Prong Creek Trib,Reach-1,6
Up Type=0
Dn Type=3
Dn Slope=0.005
Boundary for River Rch & Prof#=Prong Creek Trib,Reach-1,7
Up Type=0
Dn Type=3
Dn Slope=0.005

--- Prong Creek Trib1.g01 (geometry) ---

Geom Title=Existing Conditions

River Reach=Prong Creek Trib,Reach-1
Reach XY= 30
      1357755.00      6837038.00      1357755.00      6837138.00
      1357805.00      6837188.00      1357805.00      6837438.00
      1357855.00      6837488.00      1357905.00      6837488.00
      1357951.12      6837556.32      1357958.73      6837636.42
      1358003.14      6837694.13      1358005.17      6837717.87
      1358001.38      6837736.37      1357966.39      6837778.13
      1357962.83      6837791.40      1357974.34      6837808.01
      1358044.52      6837878.22      1358053.01      6837893.89
      1358055.48      6837912.97      1358052.63      6837982.12
      1358016.28      6838028.30      1358012.68      6838041.70
      1358027.25      6838061.85      1358052.02      6838082.48
      1358069.95      6838087.47      1358153.71      6838091.53
      1358172.13      6838104.30      1358197.00      6838131.62
      1358209.23      6838186.22      1358246.92      6838231.92
      1358253.85      6838248.47      1358255.00      6838388.00

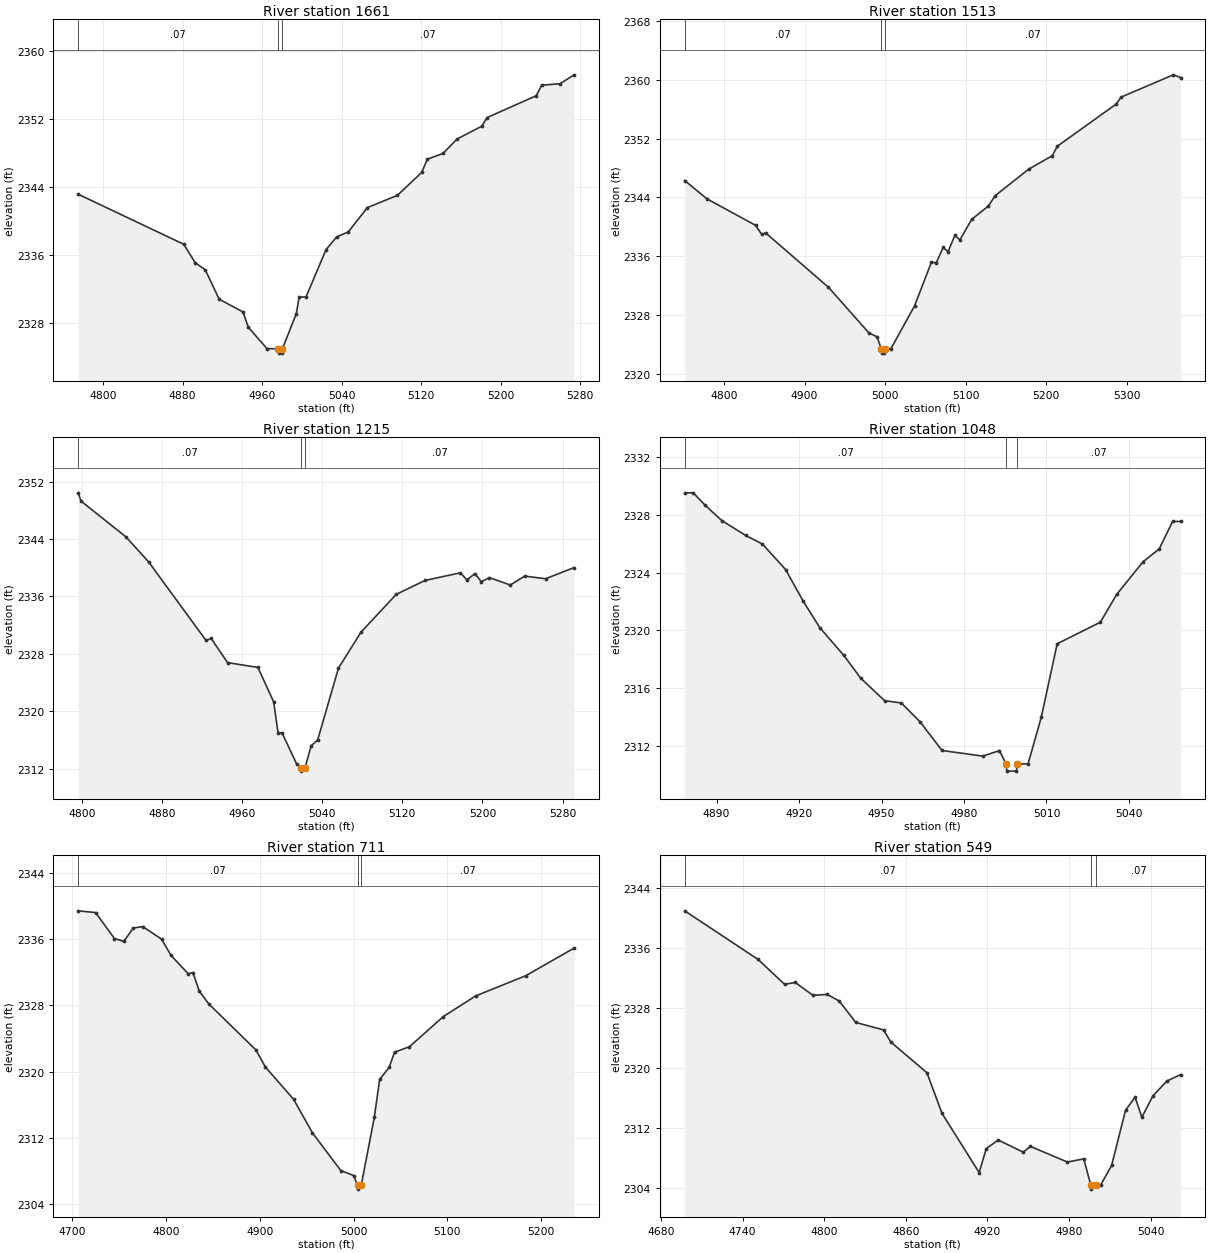
Type RM Length L Ch R = 1,1661,148,148,148
BEGIN DESCRIPTION:
Prong Creek Trib1 4055
END DESCRIPTION:
XS GIS Cut Line= 3
      1357546.53      6837145.47      1357755.00      6837060.82
      1357852.55      6836804.78
#Sta/Elev= 30
  4775.0 2343.12  4881.3 2337.22  4892.7 2335.06  4902.9 2334.21  4916.8 2330.76
  4940.8 2329.26  4946.2 2327.45  4964.9 2324.95  4976.4 2324.91  4976.7 2324.41
  4980.2 2324.41  4980.4 2324.91  4994.4 2329.04  4997.3 2331.02  5004.2 2331.02
  5024.4 2336.61  5035.1 2338.10  5046.7 2338.68  5066.0 2341.55  5096.1 2342.98
  5120.7 2345.70  5126.2 2347.24  5142.1 2347.93  5156.3 2349.63  5181.1 2351.13
  5186.4 2352.15  5235.9 2354.72  5241.3 2355.96  5259.8 2356.13  5274.0 2357.18
#Mann=3,-1,0
  4775.0    0.07       0  4976.4    0.07       0  4980.4    0.07       0
Bank Sta=4976.4,4980.4
Exp/Cntr=0.3,0.1

Type RM Length L Ch R = 1,1513,298,298,298
BEGIN DESCRIPTION:
Prong Creek Trib1 4056
END DESCRIPTION:
XS GIS Cut Line= 3
      1357557.43      6837212.73      1357805.00      6837188.00
      1358023.99      6836893.74
#Sta/Elev= 30
  4751.2 2346.31  4778.9 2343.81  4839.2 2340.21  4846.7 2338.99  4851.7 2339.18
  4929.7 2331.78  4979.9 2325.57  4990.0 2325.04  4995.5 2323.32  4995.7 2322.82
  4999.2 2322.82  4999.5 2323.32  5007.3 2323.44  5036.5 2329.24  5057.4 2335.18
  5063.6 2335.12  5072.0 2337.21  5078.2 2336.63  5086.6 2338.85  5092.8 2338.23
  5107.4 2341.01  5128.3 2342.85  5136.6 2344.24  5178.3 2347.86  5207.5 2349.68
  5213.8 2350.98  5286.7 2356.70  5293.0 2357.66  5357.7 2360.69  5366.8 2360.32
#Mann=3,-1,0
  4751.2    0.07       0  4995.5    0.07       0  4999.5    0.07       0
Bank Sta=4995.5,4999.5
Exp/Cntr=0.3,0.1

Type RM Length L Ch R = 1,1215,167,167,167
BEGIN DESCRIPTION:
Prong Creek Trib1 4057
END DESCRIPTION:
XS GIS Cut Line= 3
      1357637.75      6837503.52      1357838.76      6837471.76
      1358019.69      6837243.08
#Sta/Elev= 30
  4796.5 2350.44  4799.3 2349.29  4844.3 2344.28  4866.8 2340.81  4924.1 2329.86
  4929.2 2330.14  4945.6 2326.77  4975.9 2326.10  4991.6 2321.30  4996.0 2316.98
  5000.0 2316.98  5014.6 2312.62  5019.0 2312.14  5019.3 2311.64  5023.0 2312.14
  5029.1 2315.19  5035.5 2315.96  5056.3 2326.00  5078.8 2331.01  5114.0 2336.29
  5142.9 2338.23  5178.1 2339.29  5184.5 2338.31  5192.5 2339.17  5198.9 2338.05
  5207.0 2338.62  5227.8 2337.59  5242.2 2338.83  5263.0 2338.46  5291.6 2340.02
#Mann=3,-1,0
  4796.5    0.07       0  5019.0    0.07       0  5023.0    0.07       0
Bank Sta=5019,5023
Exp/Cntr=0.3,0.1

Type RM Length L Ch R = 1,1048,337,337,337
BEGIN DESCRIPTION:
Finn Creek Trib5T1 2.0
END DESCRIPTION:
XS GIS Cut Line= 3
      1357854.99      6837638.01      1357954.38      6837567.95
      1358004.99      6837538.01
#Sta/Elev= 30
  4878.4 2329.53  4881.5 2329.53  4885.8 2328.68  4891.9 2327.61  4900.6 2326.58
  4906.7 2325.98  4915.1 2324.22  4921.5 2322.03  4927.6 2320.18  4936.3 2318.27
  4942.4 2316.70  4951.1 2315.14  4957.2 2314.98  4964.1 2313.66  4972.0 2311.69
  4986.8 2311.30  4992.9 2311.68  4995.3 2310.76  4995.6 2310.26  4999.1 2310.26
  4999.3 2310.76  5003.3 2310.76  5008.1 2313.98  5013.9 2319.08  5029.6 2320.57
  5035.6 2322.51  5045.2 2324.77  5051.0 2325.64  5055.9 2327.55  5058.8 2327.55
#Mann=3,-1,0
  4878.4    0.07       0  4995.3    0.07       0  4999.3    0.07       0
Bank Sta=4995.3,4999.3
Exp/Cntr=0.3,0.1

Type RM Length L Ch R = 1,711,162,162,162
BEGIN DESCRIPTION:
Prong Creek Trib1 4058
END DESCRIPTION:
XS GIS Cut Line= 3
      1357726.65      6837820.37      1358018.53      6837851.16
      1358134.68      6837646.76
#Sta/Elev= 30
  4706.5 2339.39  4725.0 2339.18  4745.1 2336.05  4755.1 2335.71  4765.2 2337.31
  4775.2 2337.49  4795.3 2335.98  4805.4 2334.02  4823.7 2331.80  4828.7 2331.95
  4835.6 2329.69  4845.6 2328.17  4895.9 2322.61  4906.0 2320.55  4936.1 2316.65
  4956.2 2312.60  4986.4 2308.06  5000.0 2307.46  5004.2 2306.32  5004.4 2305.82
  5008.2 2306.32  5022.1 2314.48  5027.8 2319.05  5037.9 2320.50  5043.7 2322.34
  5059.6 2323.00  5095.7 2326.64  5130.2 2329.13  5183.5 2331.56  5235.1 2334.90
#Mann=3,-1,0
  4706.5    0.07       0  5004.2    0.07       0  5008.2    0.07       0
Bank Sta=5004.2,5008.2
Exp/Cntr=0.3,0.1

Type RM Length L Ch R = 1,549,262,262,262
BEGIN DESCRIPTION:
Finn Creek Trib5T1 1.0
END DESCRIPTION:
XS GIS Cut Line= 3
      1357754.96      6838088.01      1358043.80      6837997.81
      1358105.02      6837988.00
#Sta/Elev= 30
  4697.4 2340.93  4751.4 2334.46  4770.8 2331.16  4778.7 2331.40  4791.7 2329.69
  4802.2 2329.81  4811.1 2328.92  4823.2 2326.08  4843.6 2325.09  4848.9 2323.49
  4875.5 2319.39  4886.6 2313.98  4913.9 2306.11  4919.1 2309.30  4927.9 2310.44
  4946.3 2308.83  4951.6 2309.59  4978.8 2307.51  4990.8 2307.94  4996.0 2304.41
  4996.3 2303.91  5000.0 2304.41  5003.1 2304.41  5011.3 2307.08  5021.5 2314.40
  5028.5 2316.14  5033.5 2313.47  5041.7 2316.34  5051.9 2318.29  5062.0 2319.14
#Mann=3,-1,0
  4697.4    0.07       0  4996.0    0.07       0  5000.0    0.07       0
Bank Sta=4996,5000
Exp/Cntr=0.3,0.1

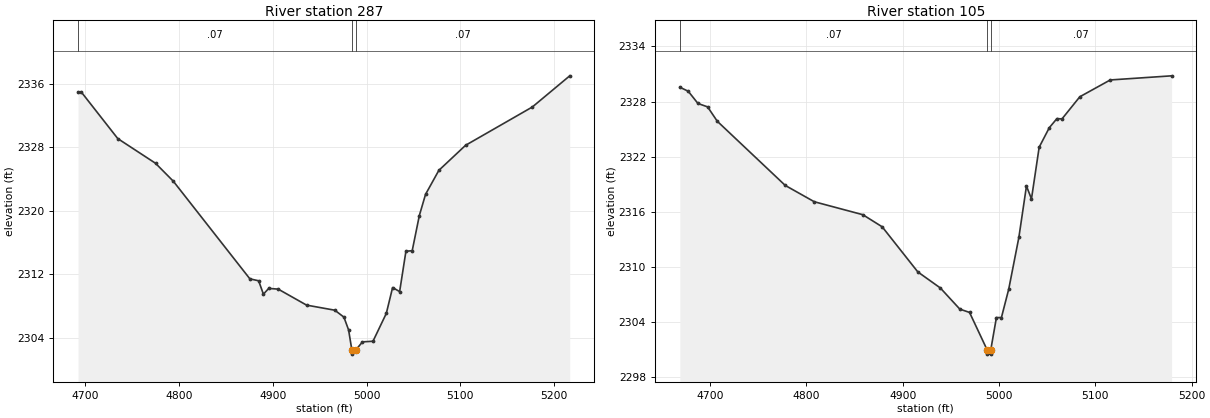
Type RM Length L Ch R = 1,287,182,182,182
BEGIN DESCRIPTION:
Prong Creek Trib1 4059
END DESCRIPTION:
XS GIS Cut Line= 3
      1357882.90      6838154.58      1358188.55      6838120.87
      1358350.82      6837977.40
#Sta/Elev= 30
  4692.5 2334.92  4696.1 2334.92  4734.9 2329.08  4775.1 2325.98  4794.1 2323.72
  4875.7 2311.45  4885.0 2311.21  4890.1 2309.53  4895.8 2310.25  4905.9 2310.16
  4936.1 2308.15  4966.2 2307.51  4975.9 2306.64  4980.9 2305.03  4984.4 2302.49
  4984.6 2301.99  4988.4 2302.49  4995.7 2303.53  5006.9 2303.61  5021.1 2307.11
  5027.8 2310.36  5035.3 2309.85  5042.0 2314.92  5048.7 2314.99  5056.3 2319.41
  5062.9 2322.07  5077.1 2325.09  5105.6 2328.24  5176.7 2333.05  5216.6 2336.97
#Mann=3,-1,0
  4692.5    0.07       0  4984.4    0.07       0  4988.4    0.07       0
Bank Sta=4984.4,4988.4
Exp/Cntr=0.3,0.1

Type RM Length L Ch R = 1,105,0,0,0
BEGIN DESCRIPTION:
Prong Creek Trib1 4060
END DESCRIPTION:
XS GIS Cut Line= 3
      1357926.36      6838243.55      1358255.53      6838282.78
      1358425.45      6838226.20
#Sta/Elev= 30
  4668.5 2329.56  4677.2 2329.12  4687.3 2327.79  4697.3 2327.42  4707.4 2325.85
  4777.9 2318.87  4808.1 2317.09  4858.5 2315.68  4878.6 2314.36  4915.6 2309.45
  4939.0 2307.70  4959.2 2305.40  4969.3 2305.04  4987.4 2301.00  4987.6 2300.50
  4991.1 2300.50  4991.4 2301.00  4997.2 2304.48  5002.4 2304.48  5010.0 2307.58
  5020.5 2313.20  5028.4 2318.80  5033.6 2317.40  5041.6 2323.03  5052.1 2325.15
  5060.0 2326.14  5065.3 2326.11  5083.8 2328.52  5115.4 2330.35  5179.1 2330.80
#Mann=3,-1,0
  4668.5    0.07       0  4987.4    0.07       0  4991.4    0.07       0
Bank Sta=4987.4,4991.4
Exp/Cntr=0.3,0.1

Chan Stop Cuts=-1