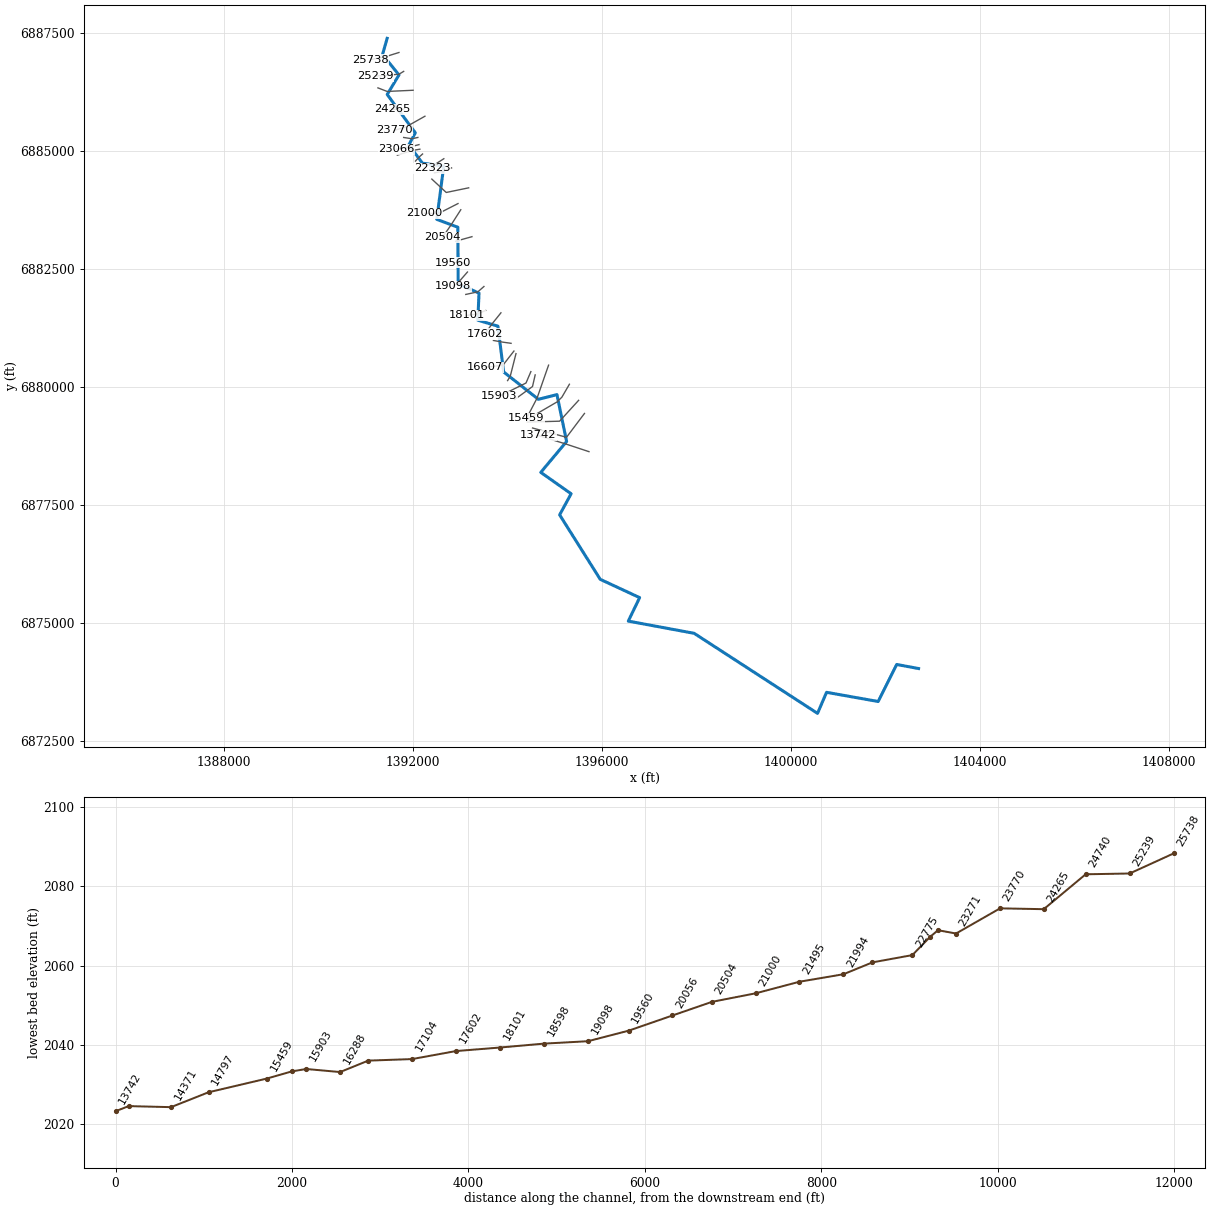
--- Rock Creek.prj (project) ---

Proj Title=Rock Creek Base Level Engineering
Current Plan=p01
Default Exp/Contr=0.3,0.1
English Units
Geom File=g01
Flow File=f01
Plan File=p01
BEGIN DESCRIPTION:
Rock Creek
END DESCRIPTION:

--- Rock Creek.p01 (plan) ---

Plan Title=Multiple Run
Short Identifier=Multiple
Geom File=g01
Flow File=f01
Subcritical Flow
K Sum by GR= 0
Std Step Tol= 0.01
Critical Tol= 0.01
Num of Std Step Trials= 20
Max Error Tol= 0.3
Flow Tol Ratio= 0.001
Split Flow NTrial= 30
Split Flow Tol= 0.02
Split Flow Ratio= 0.02
Log Output Level= 0
Friction Slope Method= 1
Unsteady Friction Slope Method= 2
Unsteady Bridges Friction Slope Method= 1
Parabolic Critical Depth
Global Vel Dist=  1 , 1 , 1
Global Log Level= 0
CheckData=True
Encroach Param= -1, 0, 0, 0
BEGIN DESCRIPTION:
Multiple Run
END DESCRIPTION:

--- Rock Creek.f01 (steady flow) ---

Flow Title=Multiple
Number of Profiles=7
Profile Names=10-year,25-year,50-year,1pct_min,100-year,1pct_plu,500-year
River Rch & RM= Rock Creek,Reach-1,25738
     282     399     497     308     615    1227     953
River Rch & RM= Rock Creek,Reach-1,24265
     457     665     843     532    1061    2116    1700
River Rch & RM= Rock Creek,Reach-1,21000
     590     867    1108     703    1403    2800    2279
River Rch & RM= Rock Creek,Reach-1,18101
     624     915    1167     738    1473    2939    2379
River Rch & RM= Rock Creek,Reach-1,13742
     668     980    1251     792    1580    3153    2554
River Rch & RM= Rock Creek,Reach-1,11423
     837    1239    1590    1011    2018    4026    3293
River Rch & RM= Rock Creek,Reach-1,5914
     899    1338    1723    1100    2194    4377    3605
River Rch & RM= Rock Creek,Reach-1,4748
     954    1423    1835    1172    2339    4667    3852
River Rch & RM= Rock Creek,Reach-1,4348
     960    1426    1834    1168    2331    4650    3816
Boundary for River Rch & Prof#=Rock Creek,Reach-1,1
Up Type=0
Dn Type=3
Dn Slope=0.005
Boundary for River Rch & Prof#=Rock Creek,Reach-1,2
Up Type=0
Dn Type=3
Dn Slope=0.005
Boundary for River Rch & Prof#=Rock Creek,Reach-1,3
Up Type=0
Dn Type=3
Dn Slope=0.005
Boundary for River Rch & Prof#=Rock Creek,Reach-1,4
Up Type=0
Dn Type=3
Dn Slope=0.005
Boundary for River Rch & Prof#=Rock Creek,Reach-1,5
Up Type=0
Dn Type=3
Dn Slope=0.005
Boundary for River Rch & Prof#=Rock Creek,Reach-1,6
Up Type=0
Dn Type=3
Dn Slope=0.005
Boundary for River Rch & Prof#=Rock Creek,Reach-1,7
Up Type=0
Dn Type=3
Dn Slope=0.005

--- Rock Creek.g01 (geometry) ---

Geom Title=Existing Conditions

River Reach=Rock Creek,Reach-1
Reach XY= 30
      1391455.00      6887388.00      1391356.88      6887043.80
      1391705.54      6886612.88      1391456.20      6886198.50
      1392051.96      6885386.64      1391914.39      6885131.39
      1392202.30      6884743.36      1392653.51      6884682.16
      1392505.24      6883553.21      1392951.49      6883386.75
      1392958.36      6882189.25      1393399.55      6881990.47
      1393374.44      6881417.44      1393799.58      6881290.68
      1393921.42      6880321.20      1394656.25      6879741.36
      1395049.66      6879840.74      1395253.93      6878848.53
      1394707.06      6878193.86      1395349.29      6877740.58
      1395106.46      6877293.77      1395965.78      6875928.32
      1396799.63      6875540.36      1396560.03      6875043.08
      1397953.54      6874784.46      1400565.64      6873088.55
      1400756.22      6873534.57      1401849.35      6873339.97
      1402241.60      6874124.53      1402705.00      6874038.00

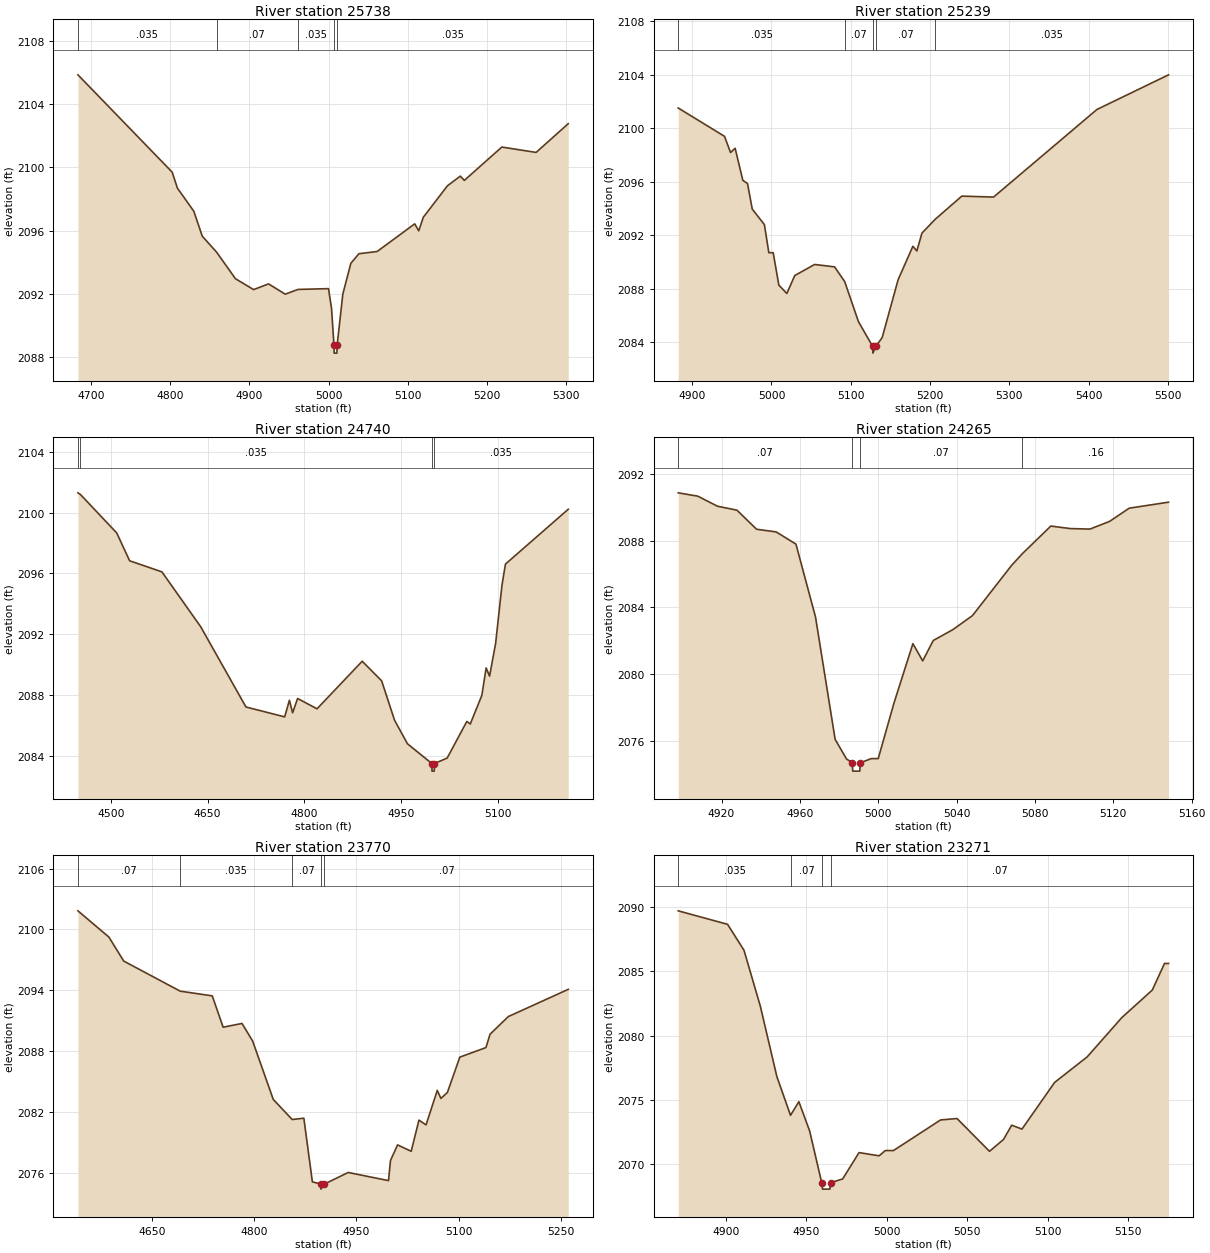
Type RM Length L Ch R = 1,25738,499,499,499
BEGIN DESCRIPTION:
Rock Creek 50.0
END DESCRIPTION:
XS GIS Cut Line= 3
      1391705.03      6887088.01      1391402.75      6886993.88
      1391105.05      6886938.01
#Sta/Elev= 30
  4683.4 2105.86  4802.5 2099.70  4809.1 2098.69  4829.8 2097.23  4840.5 2095.65
  4858.6 2094.64  4882.4 2092.96  4905.3 2092.27  4924.3 2092.63  4945.3 2091.98
  4961.4 2092.28  5000.0 2092.33  5003.8 2091.08  5006.9 2088.75  5007.1 2088.25
  5010.6 2088.25  5010.9 2088.75  5018.1 2091.99  5028.2 2093.93  5038.4 2094.54
  5061.4 2094.68  5108.9 2096.43  5114.0 2095.99  5119.8 2096.85  5150.3 2098.84
  5166.5 2099.45  5171.6 2099.18  5219.0 2101.29  5262.3 2100.95  5302.9 2102.77
#Mann=5,-1,0
  4683.4   0.035       0  4858.6    0.07       0  4961.4   0.035       0
  5006.9   0.035       0  5010.9   0.035       0
Bank Sta=5006.9,5010.9
Exp/Cntr=0.3,0.1

Type RM Length L Ch R = 1,25239,499,499,499
BEGIN DESCRIPTION:
Rock Creek 49.0
END DESCRIPTION:
XS GIS Cut Line= 3
      1391805.01      6886688.01      1391704.32      6886627.25
      1391204.96      6886588.00
#Sta/Elev= 30
  4882.4 2101.52  4940.8 2099.40  4948.4 2098.19  4954.2 2098.51  4963.9 2096.11
  4969.8 2095.87  4975.8 2093.96  4991.1 2092.80  4996.7 2090.70  5002.2 2090.70
  5009.3 2088.28  5019.4 2087.65  5029.4 2088.99  5054.4 2089.82  5079.6 2089.64
  5092.4 2088.54  5109.7 2085.55  5127.7 2083.69  5128.0 2083.19  5131.7 2083.69
  5139.7 2084.36  5159.8 2088.68  5178.4 2091.18  5183.4 2090.83  5189.9 2092.17
  5206.6 2093.20  5240.1 2094.93  5280.2 2094.86  5410.6 2101.41  5500.9 2104.00
#Mann=5,-1,0
  4882.4   0.035       0  5092.4    0.07       0  5127.7   0.035       0
  5131.7    0.07       0  5206.6   0.035       0
Bank Sta=5127.7,5131.7
Exp/Cntr=0.3,0.1

Type RM Length L Ch R = 1,24740,475,475,475
BEGIN DESCRIPTION:
Rock Creek 48.0
END DESCRIPTION:
XS GIS Cut Line= 3
      1392004.99      6886288.00      1391454.76      6886262.95
      1391260.16      6886338.62
#Sta/Elev= 30
  4449.2 2101.30  4453.1 2101.19  4509.3 2098.66  4529.3 2096.83  4579.3 2096.10
  4639.4 2092.49  4709.5 2087.21  4769.5 2086.56  4776.8 2087.65  4781.8 2086.83
  4789.5 2087.77  4819.6 2087.09  4889.6 2090.22  4919.7 2088.93  4939.7 2086.34
  4959.7 2084.79  4997.5 2083.49  4997.7 2082.99  5001.2 2082.99  5001.5 2083.49
  5021.2 2083.85  5051.7 2086.26  5057.0 2086.09  5074.9 2087.97  5081.6 2089.78
  5086.9 2089.24  5096.3 2091.40  5106.1 2095.22  5111.5 2096.61  5208.8 2100.22
#Mann=4,-1,0
  4449.2    0.07       0  4453.1   0.035       0  4997.5   0.035       0
  5001.5   0.035       0
Bank Sta=4997.5,5001.5
Exp/Cntr=0.3,0.1

Type RM Length L Ch R = 1,24265,495,495,495
BEGIN DESCRIPTION:
Rock Creek 47.0
END DESCRIPTION:
XS GIS Cut Line= 3
      1391804.96      6885888.00      1391703.03      6885882.11
      1391554.95      6885888.00
#Sta/Elev= 30
  4897.9 2090.86  4907.9 2090.66  4917.9 2090.06  4927.9 2089.82  4937.9 2088.68
  4947.9 2088.52  4958.0 2087.79  4968.0 2083.42  4978.0 2076.10  4983.8 2074.93
  4986.7 2074.70  4987.0 2074.20  4990.6 2074.20  4990.8 2074.70  4996.5 2074.95
  5000.0 2074.95  5008.0 2078.26  5017.7 2081.83  5022.7 2080.80  5028.1 2082.02
  5038.1 2082.67  5048.1 2083.51  5068.1 2086.52  5073.6 2087.22  5088.1 2088.87
  5098.1 2088.72  5108.1 2088.69  5118.1 2089.15  5128.1 2089.94  5148.2 2090.30
#Mann=4,-1,0
  4897.9    0.07       0  4986.7    0.07       0  4990.8    0.07       0
  5073.6    0.16       0
Bank Sta=4986.7,4990.8
Exp/Cntr=0.3,0.1

Type RM Length L Ch R = 1,23770,499,499,499
BEGIN DESCRIPTION:
Rock Creek 46.0
END DESCRIPTION:
XS GIS Cut Line= 3
      1392254.97      6885737.98      1391855.00      6885513.00
      1391605.01      6885438.00
#Sta/Elev= 30
  4541.1 2101.84  4586.6 2099.25  4608.3 2096.89  4691.3 2093.92  4738.3 2093.46
  4754.3 2090.37  4782.0 2090.74  4797.6 2089.01  4827.9 2083.25  4855.7 2081.27
  4872.8 2081.40  4885.3 2075.13  4897.5 2074.91  4897.9 2074.41  4903.0 2074.91
  4937.9 2076.05  4997.1 2075.25  5000.0 2077.23  5010.4 2078.77  5030.4 2078.14
  5041.8 2081.21  5052.2 2080.74  5068.7 2084.14  5074.0 2083.35  5083.5 2083.93
  5101.8 2087.42  5140.1 2088.36  5146.2 2089.68  5173.1 2091.42  5261.0 2094.10
#Mann=5,-1,0
  4541.1    0.07       0  4691.3   0.035       0  4855.7    0.07       0
  4897.5    0.07       0  4903.0    0.07       0
Bank Sta=4897.5,4903
Exp/Cntr=0.3,0.1

Type RM Length L Ch R = 1,23271,205,205,205
BEGIN DESCRIPTION:
Rock Creek 45.0
END DESCRIPTION:
XS GIS Cut Line= 3
      1392105.01      6885288.00      1391978.06      6885261.44
      1391804.99      6885288.00
#Sta/Elev= 30
  4870.3 2089.71  4901.0 2088.66  4911.2 2086.64  4921.4 2082.27  4931.6 2076.83
  4940.1 2073.81  4940.6 2073.91  4945.3 2074.87  4952.0 2072.59  4959.5 2068.57
  4960.0 2068.07  4964.6 2068.07  4965.0 2068.57  4972.5 2068.86  4982.7 2070.91
  4995.2 2070.66  4999.0 2071.07  5004.1 2071.07  5033.4 2073.45  5043.6 2073.56
  5063.8 2071.01  5072.5 2071.93  5077.6 2073.04  5084.0 2072.74  5104.3 2076.37
  5124.5 2078.35  5146.0 2081.40  5165.0 2083.55  5172.6 2085.62  5175.1 2085.62
#Mann=4,-1,0
  4870.3   0.035       0  4940.6    0.07       0  4959.5    0.07       0
  4965.0    0.07       0
Bank Sta=4959.5,4965
Exp/Cntr=0.3,0.1

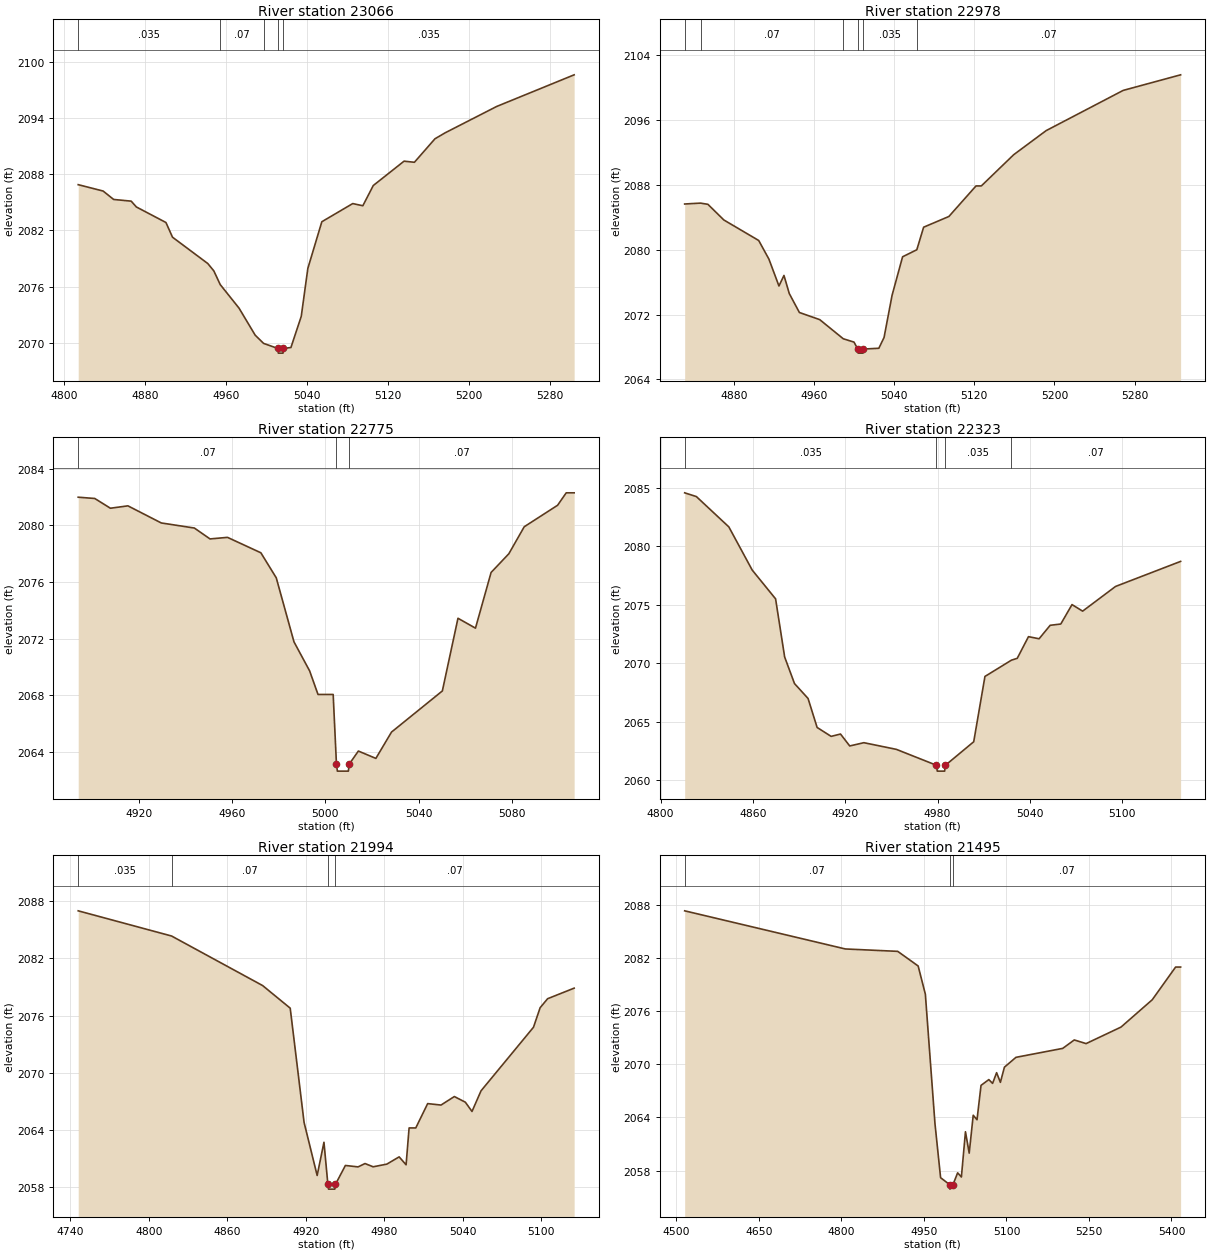
Type RM Length L Ch R = 1,23066,88,88,88
BEGIN DESCRIPTION:
Rock Creek 4285
END DESCRIPTION:
XS GIS Cut Line= 3
      1392128.88      6885136.41      1391948.58      6885090.28
      1391649.67      6885037.74
#Sta/Elev= 30
  4813.9 2086.89  4838.5 2086.21  4848.9 2085.31  4866.2 2085.13  4871.3 2084.51
  4900.5 2082.85  4907.0 2081.28  4941.8 2078.47  4947.8 2077.68  4954.1 2076.22
  4972.7 2073.70  4988.6 2070.82  4996.9 2069.94  5011.0 2069.40  5011.5 2068.90
  5016.1 2068.90  5016.5 2069.40  5023.9 2069.50  5034.1 2072.83  5040.6 2077.95
  5054.4 2082.93  5084.9 2084.87  5094.9 2084.64  5105.2 2086.80  5135.6 2089.40
  5145.8 2089.28  5166.1 2091.79  5176.2 2092.43  5227.0 2095.24  5303.5 2098.62
#Mann=5,-1,0
  4813.9   0.035       0  4954.1    0.07       0  4996.9   0.035       0
  5011.0   0.035       0  5016.5   0.035       0
Bank Sta=5011,5016.5
Exp/Cntr=0.3,0.1

Type RM Length L Ch R = 1,22978,203,203,203
BEGIN DESCRIPTION:
Rock Creek 3993
END DESCRIPTION:
XS GIS Cut Line= 3
      1392147.86      6885039.70      1391981.29      6885011.18
      1391670.38      6884913.14
#Sta/Elev= 30
  4831.0 2085.64  4846.8 2085.75  4854.2 2085.60  4870.1 2083.67  4904.9 2081.14
  4915.1 2078.84  4925.1 2075.53  4930.1 2076.83  4935.4 2074.60  4945.5 2072.26
  4965.8 2071.38  4989.3 2069.02  5000.0 2068.61  5003.8 2067.75  5004.2 2067.25
  5008.9 2067.25  5009.3 2067.75  5024.8 2067.85  5030.0 2069.18  5038.0 2074.38
  5048.5 2079.13  5062.7 2080.00  5069.5 2082.78  5094.7 2084.10  5121.8 2087.87
  5127.1 2087.87  5159.4 2091.72  5191.8 2094.69  5268.7 2099.65  5326.0 2101.57
#Mann=6,-1,0
  4831.0   0.035       0  4846.8    0.07       0  4989.3   0.035       0
  5003.8   0.035       0  5009.3   0.035       0  5062.7    0.07       0
Bank Sta=5003.8,5009.3
Exp/Cntr=0.3,0.1

Type RM Length L Ch R = 1,22775,452,452,452
BEGIN DESCRIPTION:
Rock Creek 44.0
END DESCRIPTION:
XS GIS Cut Line= 3
      1392204.99      6884937.99      1392125.38      6884868.16
      1392054.98      6884787.98
#Sta/Elev= 30
  4894.1 2082.00  4901.2 2081.91  4907.9 2081.22  4915.4 2081.39  4929.7 2080.18
  4943.9 2079.82  4950.6 2079.05  4958.1 2079.16  4972.4 2078.07  4979.0 2076.30
  4986.6 2071.77  4993.3 2069.72  4996.9 2068.05  5003.4 2068.05  5004.8 2063.13
  5005.2 2062.63  5009.9 2062.63  5010.3 2063.13  5014.2 2064.05  5021.7 2063.53
  5028.4 2065.39  5050.2 2068.30  5056.9 2073.44  5064.4 2072.74  5071.1 2076.68
  5078.7 2078.00  5085.3 2079.91  5099.6 2081.43  5103.3 2082.31  5106.7 2082.31
#Mann=3,-1,0
  4894.1    0.07       0  5004.8    0.07       0  5010.3    0.07       0
Bank Sta=5004.8,5010.3
Exp/Cntr=0.3,0.1

Type RM Length L Ch R = 1,22323,329,329,329
BEGIN DESCRIPTION:
Rock Creek 43.0
END DESCRIPTION:
XS GIS Cut Line= 3
      1392655.00      6884838.00      1392500.03      6884738.06
      1392405.00      6884638.00
#Sta/Elev= 30
  4815.6 2084.58  4823.2 2084.26  4844.3 2081.67  4859.5 2077.98  4874.7 2075.52
  4880.6 2070.55  4887.0 2068.28  4895.8 2067.01  4901.7 2064.53  4910.8 2063.77
  4916.9 2063.97  4922.9 2062.95  4932.1 2063.23  4953.2 2062.66  4979.3 2061.30
  4979.8 2060.80  4984.6 2060.80  4985.1 2061.30  5003.5 2063.31  5010.8 2068.89
  5028.0 2070.28  5031.8 2070.44  5039.1 2072.29  5046.0 2072.11  5053.2 2073.26
  5060.1 2073.37  5067.4 2075.03  5074.3 2074.47  5095.7 2076.58  5138.0 2078.72
#Mann=4,-1,0
  4815.6   0.035       0  4979.3   0.035       0  4985.1   0.035       0
  5028.0    0.07       0
Bank Sta=4979.3,4985.1
Exp/Cntr=0.3,0.1

Type RM Length L Ch R = 1,21994,499,499,499
BEGIN DESCRIPTION:
Rock Creek 42.0
END DESCRIPTION:
XS GIS Cut Line= 3
      1392818.45      6884643.37      1392577.90      6884561.50
      1392455.03      6884538.01
#Sta/Elev= 30
  4745.9 2086.97  4817.3 2084.33  4886.9 2079.14  4908.0 2076.77  4918.6 2064.80
  4928.6 2059.24  4933.8 2062.72  4936.8 2058.31  4937.3 2057.81  4942.1 2057.81
  4942.6 2058.31  4950.2 2060.29  4959.9 2060.14  4965.2 2060.49  4971.4 2060.15
  4981.9 2060.43  4991.3 2061.19  4996.6 2060.36  4998.9 2064.22  5004.0 2064.22
  5013.1 2066.77  5023.3 2066.62  5033.5 2067.51  5041.9 2066.92  5047.0 2065.95
  5053.9 2068.11  5094.0 2074.77  5099.1 2076.82  5104.8 2077.76  5125.1 2078.87
#Mann=4,-1,0
  4745.9   0.035       0  4817.3    0.07       0  4936.8    0.07       0
  4942.6    0.07       0
Bank Sta=4936.8,4942.6
Exp/Cntr=0.3,0.1

Type RM Length L Ch R = 1,21495,495,495,495
BEGIN DESCRIPTION:
Rock Creek 41.0
END DESCRIPTION:
XS GIS Cut Line= 3
      1393180.54      6884221.34      1392705.73      6884122.94
      1392400.62      6884406.61
#Sta/Elev= 30
  4515.1 2087.30  4807.2 2083.00  4902.4 2082.73  4939.5 2081.08  4952.6 2077.90
  4970.1 2063.29  4980.3 2057.21  4996.9 2056.42  4997.4 2055.92  5002.8 2056.42
  5011.3 2057.76  5018.1 2057.29  5025.5 2062.39  5032.3 2059.98  5039.6 2064.25
  5046.5 2063.74  5053.8 2067.62  5068.0 2068.27  5074.8 2067.84  5082.1 2069.05
  5089.0 2067.96  5096.3 2069.67  5117.3 2070.78  5202.3 2071.79  5223.3 2072.74
  5244.8 2072.33  5308.2 2074.19  5365.0 2077.27  5407.5 2080.96  5416.6 2080.96
#Mann=3,-1,0
  4515.1    0.07       0  4996.9    0.07       0  5002.8    0.07       0
Bank Sta=4996.9,5002.8
Exp/Cntr=0.3,0.1

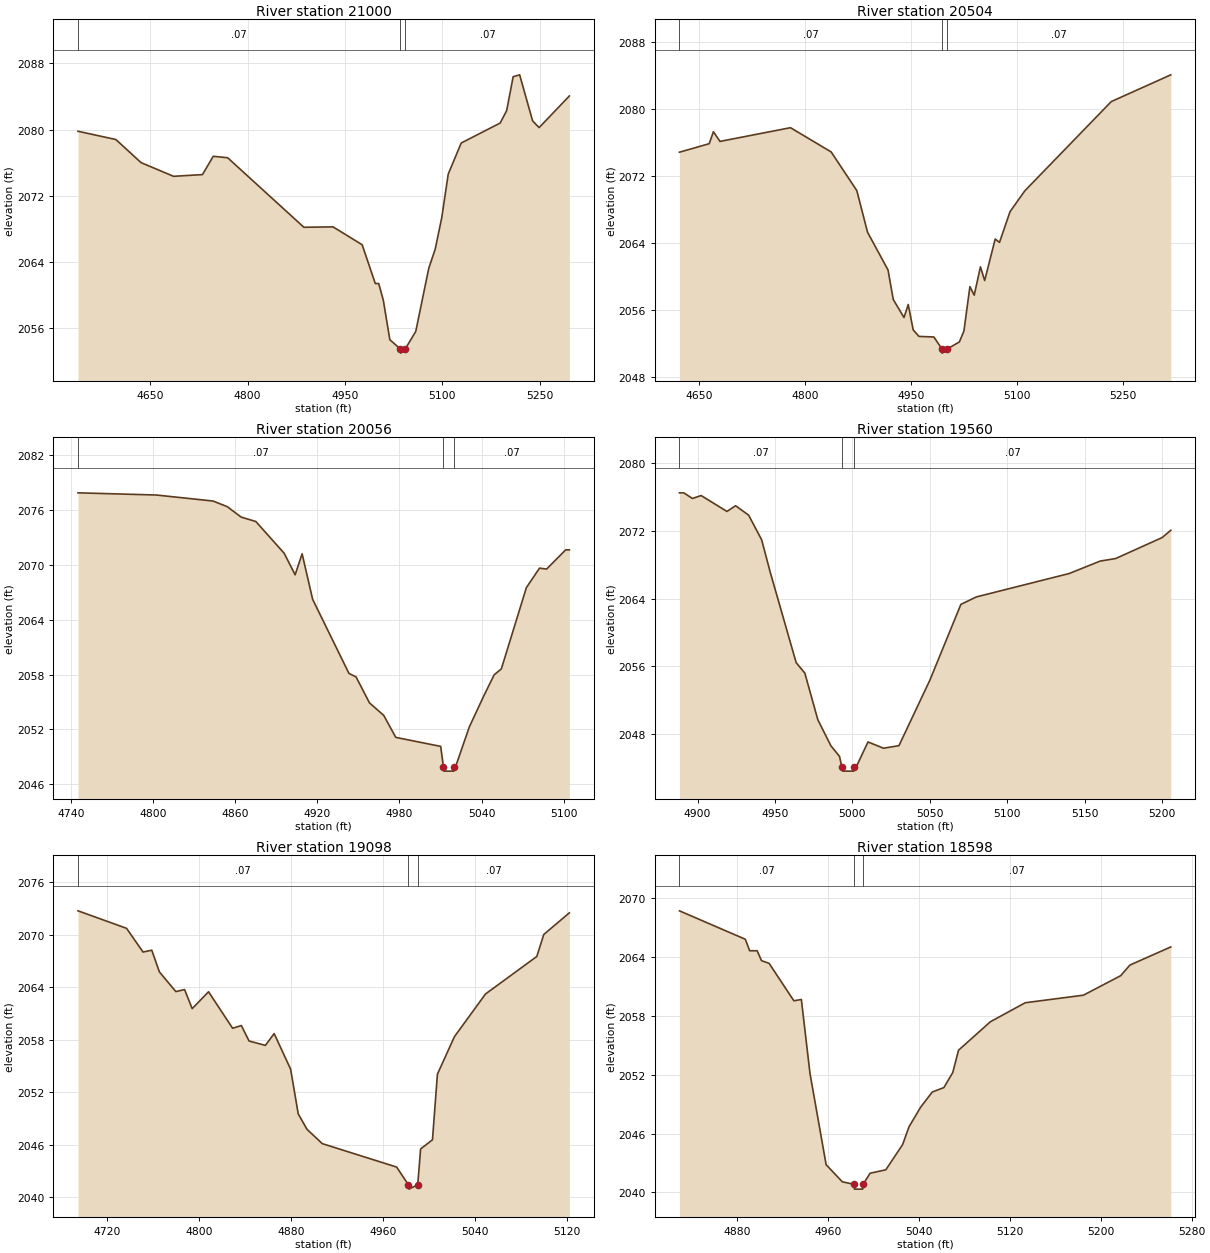
Type RM Length L Ch R = 1,21000,496,496,496
BEGIN DESCRIPTION:
Rock Creek 40.0
END DESCRIPTION:
XS GIS Cut Line= 3
      1392955.01      6883888.01      1392544.10      6883678.37
      1392248.42      6883682.10
#Sta/Elev= 30
  4538.7 2079.79  4597.1 2078.79  4635.9 2076.00  4686.0 2074.35  4730.5 2074.56
  4747.1 2076.77  4769.3 2076.59  4886.7 2068.20  4931.6 2068.25  4976.5 2066.09
  4996.7 2061.41  5002.0 2061.41  5009.1 2059.39  5019.1 2054.63  5035.4 2053.51
  5035.9 2053.01  5042.9 2053.51  5059.1 2055.64  5079.1 2063.25  5089.1 2065.58
  5099.1 2069.36  5109.1 2074.62  5129.1 2078.37  5189.1 2080.78  5199.1 2082.28
  5209.1 2086.37  5219.1 2086.60  5239.1 2081.04  5249.1 2080.23  5295.7 2084.05
#Mann=3,-1,0
  4538.7    0.07       0  5035.4    0.07       0  5042.9    0.07       0
Bank Sta=5035.4,5042.9
Exp/Cntr=0.3,0.1

Type RM Length L Ch R = 1,20504,448,448,448
BEGIN DESCRIPTION:
Rock Creek 39.0
END DESCRIPTION:
XS GIS Cut Line= 3
      1393013.87      6883756.79      1392810.04      6883438.10
      1392629.77      6883176.99
#Sta/Elev= 30
  4621.7 2074.88  4663.9 2075.90  4669.8 2077.33  4679.1 2076.17  4778.9 2077.81
  4836.5 2074.91  4872.8 2070.29  4888.0 2065.31  4917.0 2060.80  4924.4 2057.27
  4939.6 2055.12  4945.6 2056.67  4952.6 2053.64  4960.8 2052.86  4981.9 2052.79
  4993.3 2051.36  4993.8 2050.86  5000.9 2051.36  5018.0 2052.20  5024.4 2053.50
  5032.9 2058.81  5039.0 2057.79  5047.8 2061.17  5053.8 2059.54  5068.7 2064.50
  5074.8 2064.10  5089.7 2067.77  5110.6 2070.26  5233.0 2080.93  5317.3 2084.13
#Mann=3,-1,0
  4621.7    0.07       0  4993.3    0.07       0  5000.9    0.07       0
Bank Sta=4993.3,5000.9
Exp/Cntr=0.3,0.1

Type RM Length L Ch R = 1,20056,496,496,496
BEGIN DESCRIPTION:
Rock Creek 38.0
END DESCRIPTION:
XS GIS Cut Line= 3
      1393250.10      6883186.35      1393004.68      6883117.87
      1392904.96      6883087.99
#Sta/Elev= 30
  4745.2 2077.91  4802.4 2077.67  4843.9 2077.01  4854.3 2076.39  4864.4 2075.25
  4875.1 2074.77  4895.8 2071.29  4903.8 2068.93  4908.9 2071.23  4916.6 2066.24
  4943.1 2058.13  4948.3 2057.74  4958.1 2054.90  4968.5 2053.53  4977.3 2051.12
  5010.1 2050.13  5012.1 2047.92  5012.6 2047.42  5019.6 2047.42  5020.1 2047.92
  5021.4 2048.08  5031.0 2052.25  5041.4 2055.60  5049.2 2057.98  5054.4 2058.61
  5072.7 2067.52  5082.3 2069.66  5087.5 2069.56  5101.4 2071.66  5104.1 2071.66
#Mann=3,-1,0
  4745.2    0.07       0  5012.1    0.07       0  5020.1    0.07       0
Bank Sta=5012.1,5020.1
Exp/Cntr=0.3,0.1

Type RM Length L Ch R = 1,19560,462,462,462
BEGIN DESCRIPTION:
Rock Creek 37.0
END DESCRIPTION:
XS GIS Cut Line= 3
      1393154.98      6882588.01      1393055.08      6882637.97
      1392849.38      6882637.66
#Sta/Elev= 30
  4888.3 2076.51  4891.1 2076.51  4896.7 2075.84  4902.3 2076.19  4919.0 2074.31
  4924.6 2074.98  4933.0 2073.87  4941.4 2070.96  4947.0 2067.09  4963.7 2056.43
  4969.3 2055.19  4977.7 2049.68  4986.1 2046.61  4991.7 2045.34  4993.2 2044.10
  4993.7 2043.60  5000.8 2043.60  5001.3 2044.10  5002.5 2044.10  5010.1 2047.05
  5020.1 2046.31  5030.1 2046.61  5050.1 2054.37  5070.1 2063.32  5080.1 2064.20
  5140.1 2066.97  5160.1 2068.44  5170.1 2068.74  5200.1 2071.22  5205.7 2072.08
#Mann=3,-1,0
  4888.3    0.07       0  4993.2    0.07       0  5001.3    0.07       0
Bank Sta=4993.2,5001.3
Exp/Cntr=0.3,0.1

Type RM Length L Ch R = 1,19098,500,500,500
BEGIN DESCRIPTION:
Rock Creek 36.0
END DESCRIPTION:
XS GIS Cut Line= 3
      1393154.99      6882437.99      1392954.74      6882207.94
      1392855.01      6882138.01
#Sta/Elev= 30
  4695.0 2072.75  4737.2 2070.75  4751.5 2068.04  4759.1 2068.25  4765.7 2065.77
  4780.0 2063.52  4787.6 2063.75  4794.2 2061.57  4808.4 2063.50  4829.3 2059.33
  4836.9 2059.64  4843.6 2057.87  4857.8 2057.37  4865.4 2058.72  4879.7 2054.65
  4886.3 2049.54  4893.9 2047.78  4907.2 2046.14  4971.8 2043.46  4982.0 2041.44
  4982.5 2040.94  4990.1 2041.44  4992.6 2045.53  5002.9 2046.58  5007.2 2054.08
  5022.0 2058.37  5049.0 2063.25  5093.5 2067.53  5099.6 2070.05  5121.8 2072.52
#Mann=3,-1,0
  4695.0    0.07       0  4982.0    0.07       0  4990.1    0.07       0
Bank Sta=4982,4990.1
Exp/Cntr=0.3,0.1

Type RM Length L Ch R = 1,18598,497,497,497
BEGIN DESCRIPTION:
Rock Creek 35.0
END DESCRIPTION:
XS GIS Cut Line= 4
      1393503.93      6882130.92      1393455.00      6882088.00
      1393375.53      6882018.29      1393119.82      6881963.06
#Sta/Elev= 30
  4829.2 2068.70  4887.2 2065.80  4891.0 2064.63  4897.6 2064.63  4901.4 2063.62
  4908.1 2063.35  4929.9 2059.53  4936.5 2059.66  4944.1 2052.11  4958.3 2042.82
  4972.6 2041.07  4982.7 2040.83  4983.2 2040.33  4990.4 2040.33  4990.9 2040.83
  4997.0 2041.95  5010.8 2042.30  5025.6 2044.87  5031.2 2046.68  5041.5 2048.69
  5051.7 2050.23  5061.9 2050.68  5069.7 2052.21  5074.8 2054.49  5102.8 2057.39
  5133.5 2059.33  5184.7 2060.10  5217.5 2062.09  5225.6 2063.17  5261.6 2065.02
#Mann=3,-1,0
  4829.2    0.07       0  4982.7    0.07       0  4990.9    0.07       0
Bank Sta=4982.7,4990.9
Exp/Cntr=0.3,0.1

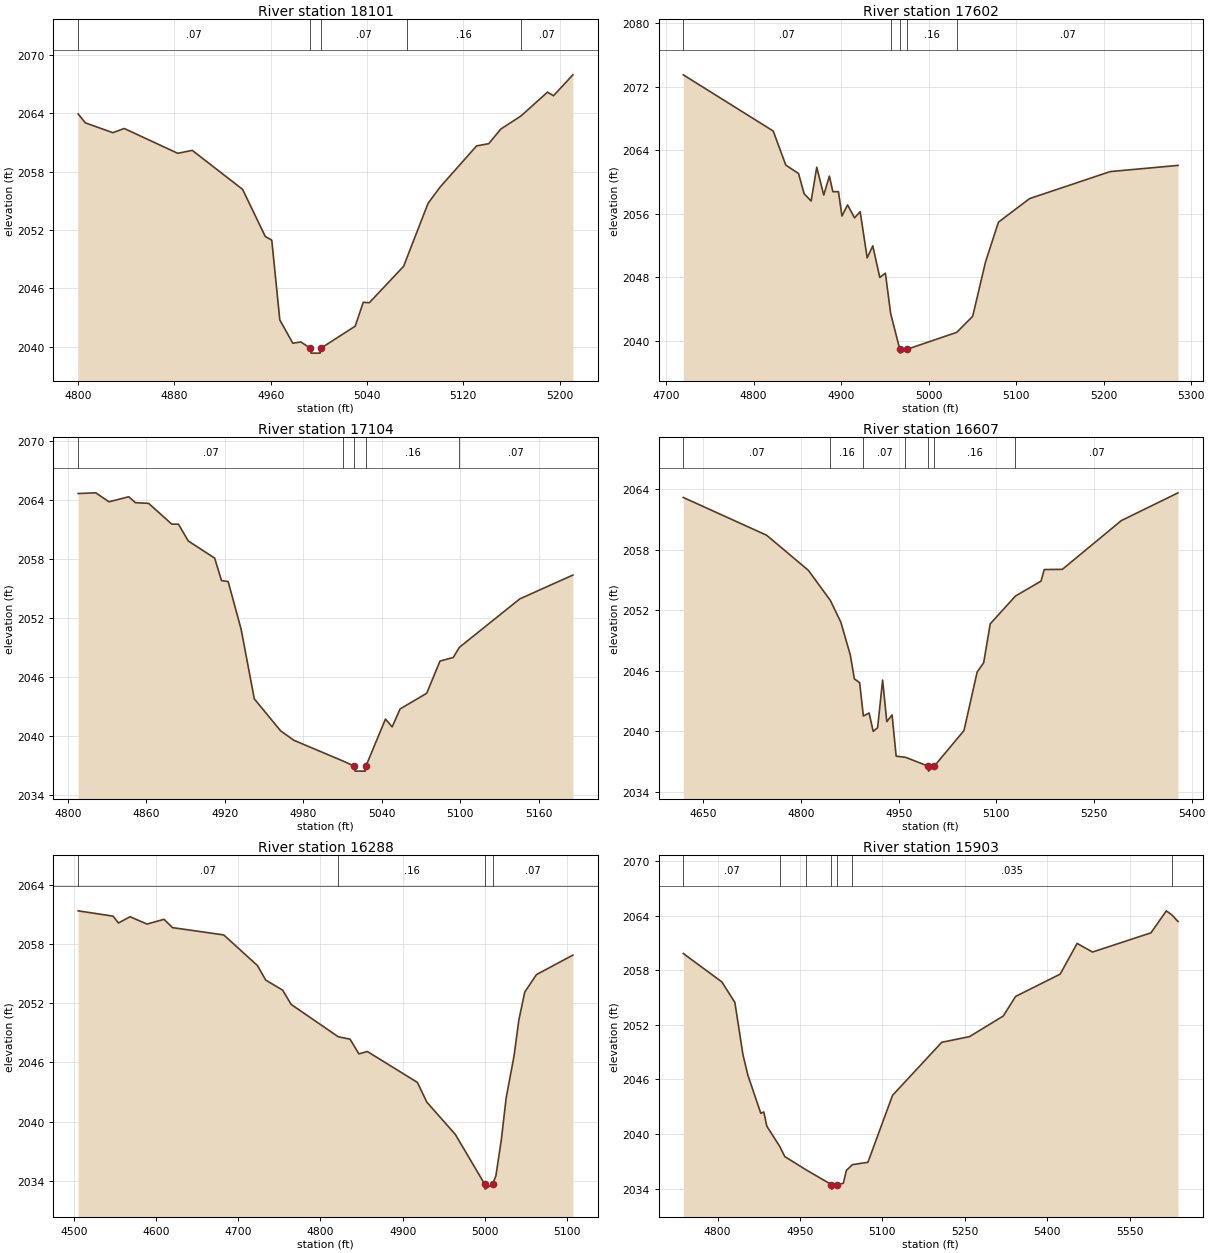
Type RM Length L Ch R = 1,18101,499,499,499
BEGIN DESCRIPTION:
Rock Creek 34.0
END DESCRIPTION:
XS GIS Cut Line= 4
      1393540.54      6881622.21      1393455.00      6881588.00
      1393354.94      6881547.98      1393145.71      6881520.71
#Sta/Elev= 30
  4800.1 2063.95  4806.1 2063.03  4828.9 2062.02  4838.4 2062.45  4882.8 2059.90
  4894.9 2060.20  4936.7 2056.19  4955.5 2051.35  4960.9 2050.97  4967.6 2042.76
  4978.4 2040.37  4985.1 2040.50  4993.0 2039.85  4993.5 2039.35  5001.1 2039.35
  5001.6 2039.85  5030.2 2042.12  5036.9 2044.58  5041.9 2044.53  5070.5 2048.29
  5072.9 2049.08  5090.7 2054.75  5100.8 2056.44  5131.0 2060.66  5141.1 2060.89
  5151.2 2062.40  5167.9 2063.74  5189.9 2066.19  5194.9 2065.82  5211.0 2067.97
#Mann=5,-1,0
  4800.1    0.07       0  4993.0    0.07       0  5001.6    0.07       0
  5072.9    0.16       0  5167.9    0.07       0
Bank Sta=4993,5001.6
Exp/Cntr=0.3,0.1

Type RM Length L Ch R = 1,17602,498,498,498
BEGIN DESCRIPTION:
Rock Creek 33.0
END DESCRIPTION:
XS GIS Cut Line= 4
      1393863.85      6881573.70      1393755.00      6881438.00
      1393688.53      6881355.13      1393521.54      6881124.42
#Sta/Elev= 30
  4719.8 2073.52  4822.5 2066.44  4836.9 2062.14  4851.4 2061.09  4857.8 2058.54
  4865.8 2057.62  4872.2 2061.88  4880.2 2058.37  4886.6 2060.76  4890.6 2058.80
  4897.0 2058.80  4901.0 2055.73  4907.4 2057.13  4915.4 2055.50  4921.8 2056.28
  4929.8 2050.46  4936.2 2051.97  4944.2 2047.99  4950.6 2048.53  4956.6 2043.46
  4967.0 2038.96  4967.5 2038.46  4975.7 2038.96  5032.1 2041.08  5050.3 2043.10
  5065.0 2049.97  5079.7 2054.96  5115.3 2057.93  5207.3 2061.33  5284.8 2062.11
#Mann=5,-1,0
  4719.8    0.07       0  4956.6    0.16       0  4967.0    0.07       0
  4975.7    0.16       0  5032.1    0.07       0
Bank Sta=4967,4975.7
Exp/Cntr=0.3,0.1

Type RM Length L Ch R = 1,17104,497,497,497
BEGIN DESCRIPTION:
Rock Creek 32.0
END DESCRIPTION:
XS GIS Cut Line= 4
      1394078.40      6880927.59      1394005.00      6880938.00
      1393888.11      6880954.57      1393705.03      6880987.99
#Sta/Elev= 30
  4807.8 2064.63  4821.3 2064.70  4831.4 2063.79  4846.5 2064.30  4851.6 2063.70
  4861.7 2063.63  4879.4 2061.52  4884.5 2061.52  4892.0 2059.81  4912.2 2058.07
  4917.4 2055.79  4922.5 2055.69  4932.4 2050.86  4942.5 2043.78  4962.7 2040.52
  4972.8 2039.57  5010.6 2037.45  5019.1 2036.94  5019.6 2036.44  5027.3 2036.44
  5027.8 2036.94  5042.8 2041.73  5047.9 2040.93  5054.0 2042.76  5074.3 2044.34
  5084.5 2047.62  5094.6 2047.98  5099.3 2049.01  5145.5 2053.93  5186.1 2056.35
#Mann=5,-1,0
  4807.8    0.07       0  5010.6    0.16       0  5019.1    0.07       0
  5027.8    0.16       0  5099.3    0.07       0
Bank Sta=5019.1,5027.8
Exp/Cntr=0.3,0.1

Type RM Length L Ch R = 1,16607,319,319,319
BEGIN DESCRIPTION:
Rock Creek 31.0
END DESCRIPTION:
XS GIS Cut Line= 3
      1394138.94      6880763.57      1393904.97      6880462.99
      1393528.47      6880418.70
#Sta/Elev= 30
  4619.1 2063.16  4747.1 2059.42  4811.3 2055.94  4845.1 2052.95  4861.1 2050.81
  4875.6 2047.57  4881.9 2045.19  4890.0 2044.81  4895.7 2041.51  4904.5 2041.81
  4910.8 2039.99  4917.6 2040.35  4925.3 2045.07  4931.7 2040.95  4939.8 2041.62
  4946.1 2037.53  4960.4 2037.42  4995.2 2036.55  4995.7 2036.05  5004.7 2036.55
  5050.3 2040.07  5070.5 2045.87  5080.5 2046.78  5090.6 2050.64  5129.4 2053.40
  5168.6 2054.87  5173.6 2056.02  5201.4 2056.04  5292.0 2060.87  5379.1 2063.62
#Mann=7,-1,0
  4619.1    0.07       0  4845.1    0.16       0  4895.7    0.07       0
  4960.4    0.16       0  4995.2    0.07       0  5004.7    0.16       0
  5129.4    0.07       0
Bank Sta=4995.2,5004.7
Exp/Cntr=0.3,0.1

Type RM Length L Ch R = 1,16288,385,385,385
BEGIN DESCRIPTION:
Rock Creek 30.0
END DESCRIPTION:
XS GIS Cut Line= 3
      1394182.34      6880709.29      1394060.91      6880229.51
      1394005.02      6880138.04
#Sta/Elev= 30
  4505.1 2061.34  4547.7 2060.80  4554.1 2060.11  4568.3 2060.74  4588.9 2060.00
  4609.6 2060.48  4619.9 2059.64  4682.3 2058.90  4723.3 2055.80  4733.4 2054.33
  4754.0 2053.31  4764.3 2051.87  4821.7 2048.59  4836.0 2048.35  4846.8 2046.86
  4857.1 2047.10  4918.0 2043.97  4929.4 2041.98  4964.2 2038.70  4999.9 2033.67
  5000.4 2033.17  5009.4 2033.67  5013.5 2034.51  5020.1 2038.16  5026.0 2042.41
  5035.6 2046.66  5041.4 2050.27  5048.6 2053.11  5062.8 2054.88  5107.2 2056.86
#Mann=4,-1,0
  4505.1    0.07       0  4821.7    0.16       0  4999.9    0.07       0
  5009.4    0.07       0
Bank Sta=4999.9,5009.4
Exp/Cntr=0.3,0.1

Type RM Length L Ch R = 1,15903,162,162,162
BEGIN DESCRIPTION:
Rock Creek 3994
END DESCRIPTION:
XS GIS Cut Line= 3
      1394497.55      6880327.87      1394394.45      6880086.68
      1393822.87      6879802.58
#Sta/Elev= 30
  4737.7 2059.84  4808.0 2056.71  4831.6 2054.46  4846.3 2048.72  4855.2 2046.48
  4878.8 2042.27  4884.2 2042.42  4889.8 2040.85  4913.3 2038.63  4922.4 2037.52
  4961.8 2036.04  5007.4 2034.44  5007.9 2033.94  5017.1 2034.44  5029.0 2034.58
  5034.6 2036.00  5045.5 2036.63  5073.8 2036.89  5118.6 2044.25  5208.2 2050.08
  5258.6 2050.70  5320.2 2052.97  5342.6 2055.12  5423.7 2057.57  5454.6 2060.95
  5482.6 2060.00  5589.0 2062.11  5617.0 2064.53  5627.3 2064.07  5638.3 2063.36
#Mann=7,-1,0
  4737.7    0.07       0  4913.3   0.035       0  4961.8    0.16       0
  5007.4    0.07       0  5017.1    0.16       0  5045.5   0.035       0
  5627.3    0.07       0
Bank Sta=5007.4,5017.1
Exp/Cntr=0.3,0.1

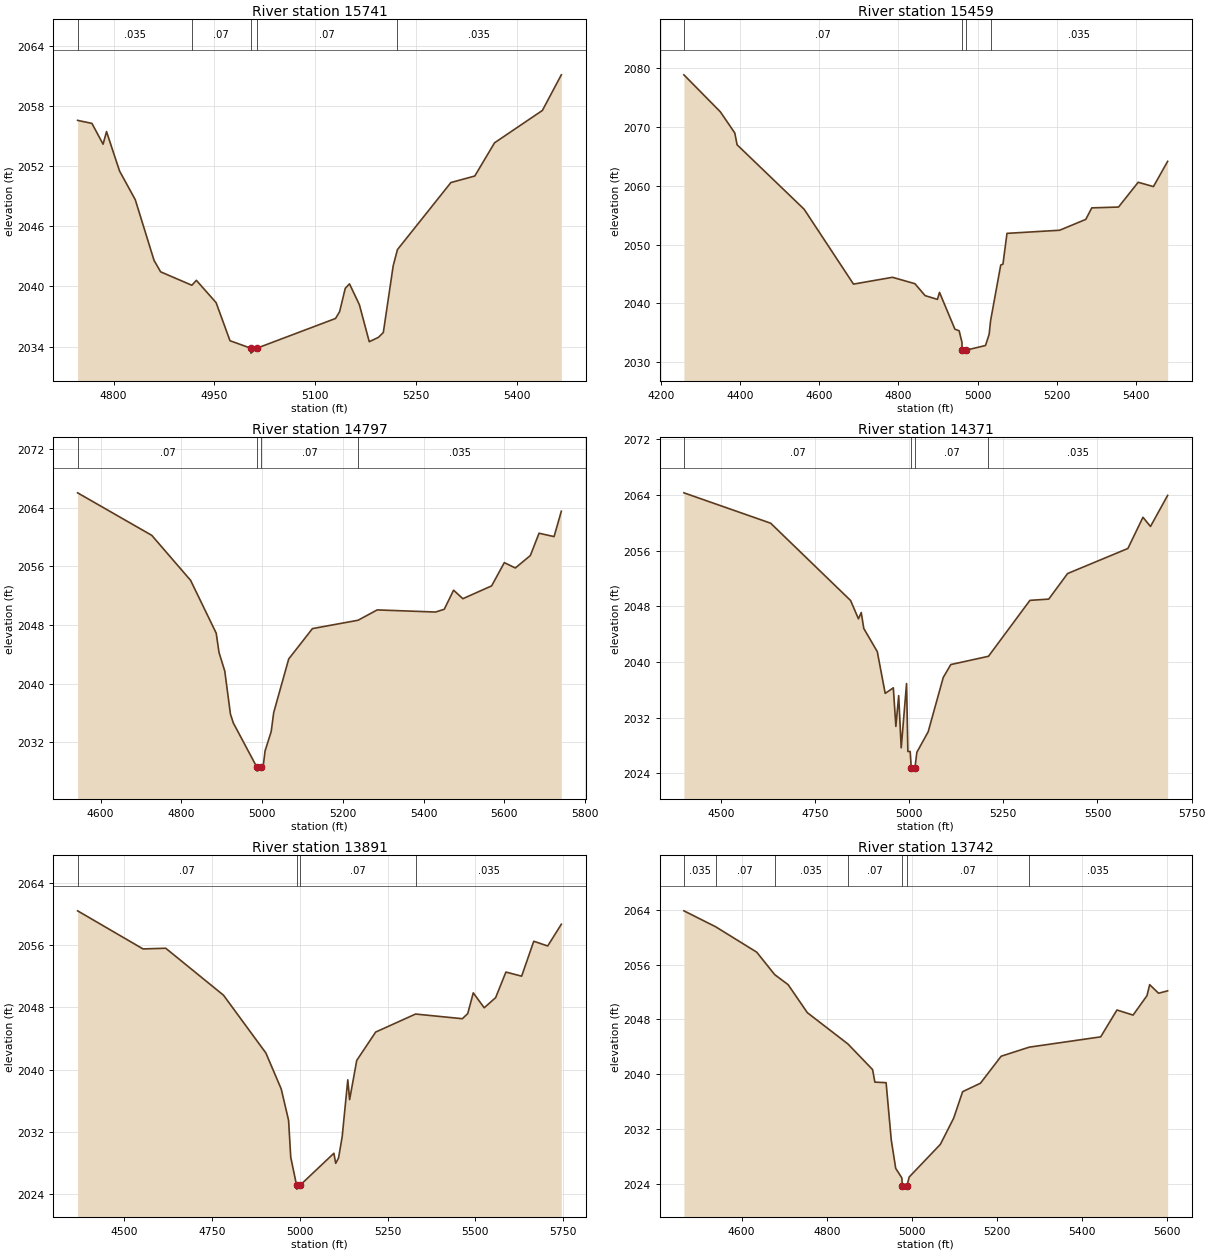
Type RM Length L Ch R = 1,15741,282,282,282
BEGIN DESCRIPTION:
Rock Creek 29.0
END DESCRIPTION:
XS GIS Cut Line= 3
      1394588.76      6880258.78      1394531.89      6880011.74
      1394155.01      6879738.01
#Sta/Elev= 30
  4746.5 2056.59  4767.8 2056.29  4784.4 2054.21  4789.5 2055.47  4808.9 2051.53
  4832.3 2048.66  4860.2 2042.60  4870.0 2041.46  4916.4 2040.12  4923.1 2040.61
  4952.5 2038.38  4973.1 2034.58  5003.7 2033.84  5004.2 2033.34  5013.4 2033.84
  5130.0 2036.80  5136.1 2037.48  5144.5 2039.81  5150.8 2040.26  5165.5 2038.18
  5180.2 2034.48  5193.9 2034.92  5201.1 2035.40  5215.8 2042.07  5222.1 2043.68
  5301.6 2050.38  5337.1 2051.03  5366.5 2054.35  5437.6 2057.58  5465.8 2061.14
#Mann=5,-1,0
  4746.5   0.035       0  4916.4    0.07       0  5003.7    0.07       0
  5013.4    0.07       0  5222.1   0.035       0
Bank Sta=5003.7,5013.4
Exp/Cntr=0.3,0.1

Type RM Length L Ch R = 1,15459,662,662,662
BEGIN DESCRIPTION:
Rock Creek 28.0
END DESCRIPTION:
XS GIS Cut Line= 3
      1394872.22      6880465.02      1394627.66      6879763.95
      1394405.02      6879338.04
#Sta/Elev= 30
  4257.5 2078.92  4349.7 2072.62  4386.2 2069.02  4392.0 2067.01  4561.5 2056.04
  4686.3 2043.29  4784.8 2044.45  4841.6 2043.36  4867.4 2041.33  4898.5 2040.69
  4903.8 2041.88  4942.8 2035.61  4953.4 2035.35  4960.6 2033.37  4961.0 2032.04
  4961.5 2031.54  4970.7 2032.04  5020.1 2032.84  5029.3 2034.74  5033.0 2037.08
  5058.6 2046.54  5064.2 2046.68  5074.4 2051.93  5207.5 2052.46  5273.7 2054.31
  5288.8 2056.27  5356.4 2056.41  5406.2 2060.63  5444.7 2059.89  5480.6 2064.19
#Mann=4,-1,0
  4257.5    0.07       0  4961.0    0.07       0  4970.7    0.07       0
  5033.0   0.035       0
Bank Sta=4961,4970.7
Exp/Cntr=0.3,0.1

Type RM Length L Ch R = 1,14797,426,426,426
BEGIN DESCRIPTION:
Rock Creek 27.0
END DESCRIPTION:
XS GIS Cut Line= 4
      1395313.01      6880060.48      1395155.00      6879788.00
      1395054.60      6879687.83      1394414.52      6879313.90
#Sta/Elev= 30
  4543.2 2066.04  4726.9 2060.24  4823.0 2054.11  4886.5 2046.90  4893.5 2044.26
  4907.7 2041.73  4921.8 2035.85  4928.9 2034.65  4987.6 2028.58  4988.1 2028.08
  4997.4 2028.58  5002.7 2028.66  5007.5 2030.83  5022.7 2033.47  5028.9 2036.07
  5066.1 2043.38  5124.8 2047.52  5237.9 2048.66  5285.2 2050.07  5429.9 2049.78
  5451.4 2050.16  5474.4 2052.76  5497.5 2051.60  5568.7 2053.35  5600.1 2056.52
  5627.4 2055.79  5664.6 2057.49  5686.1 2060.53  5723.3 2060.07  5741.3 2063.53
#Mann=4,-1,0
  4543.2    0.07       0  4987.6    0.07       0  4997.4    0.07       0
  5237.9   0.035       0
Bank Sta=4987.6,4997.4
Exp/Cntr=0.3,0.1

Type RM Length L Ch R = 1,14371,480,480,480
BEGIN DESCRIPTION:
Rock Creek 26.0
END DESCRIPTION:
XS GIS Cut Line= 3
      1395508.31      6879719.75      1395105.45      6879277.81
      1394419.49      6879259.68
#Sta/Elev= 30
  4402.0 2064.29  4632.3 2059.93  4844.5 2048.83  4865.4 2046.20  4872.8 2047.10
  4879.6 2044.81  4915.4 2041.49  4936.4 2035.49  4958.0 2036.29  4964.7 2030.75
  4972.2 2035.17  4978.9 2027.67  4993.1 2036.90  4996.6 2027.15  5002.7 2027.15
  5005.6 2024.83  5006.1 2024.33  5015.4 2024.83  5020.5 2027.04  5050.5 2029.98
  5090.5 2037.78  5110.5 2039.63  5210.6 2040.82  5320.6 2048.85  5370.6 2049.03
  5420.6 2052.70  5580.7 2056.30  5620.7 2060.78  5640.7 2059.46  5686.2 2063.92
#Mann=4,-1,0
  4402.0    0.07       0  5005.6    0.07       0  5015.4    0.07       0
  5210.6   0.035       0
Bank Sta=5005.6,5015.4
Exp/Cntr=0.3,0.1

Type RM Length L Ch R = 1,13891,149,149,149
BEGIN DESCRIPTION:
Rock Creek 25.0
END DESCRIPTION:
XS GIS Cut Line= 3
      1395631.99      6879441.95      1395251.63      6878936.72
      1394533.17      6879133.41
#Sta/Elev= 30
  4367.6 2060.45  4553.9 2055.54  4618.5 2055.63  4783.0 2049.58  4903.7 2042.13
  4947.4 2037.49  4968.3 2033.46  4974.5 2028.69  4991.1 2025.09  4991.6 2024.59
  5001.0 2025.09  5097.3 2029.21  5102.5 2027.91  5110.6 2028.61  5120.9 2031.33
  5136.9 2038.68  5142.1 2036.12  5162.4 2041.18  5216.3 2044.83  5329.9 2047.15
  5463.1 2046.55  5478.4 2047.21  5494.2 2049.88  5525.3 2047.96  5557.8 2049.26
  5587.1 2052.56  5631.9 2052.03  5666.4 2056.53  5706.1 2055.92  5744.9 2058.72
#Mann=4,-1,0
  4367.6    0.07       0  4991.1    0.07       0  5001.0    0.07       0
  5329.9   0.035       0
Bank Sta=4991.1,5001
Exp/Cntr=0.3,0.1

Type RM Length L Ch R = 1,13742,349,349,349
BEGIN DESCRIPTION:
Rock Creek 3992
END DESCRIPTION:
XS GIS Cut Line= 3
      1395727.51      6878632.49      1395219.16      6878800.81
      1394644.62      6878977.54
#Sta/Elev= 30
  4464.5 2063.82  4539.1 2061.50  4635.7 2057.80  4677.7 2054.54  4709.4 2053.07
  4754.6 2048.99  4850.0 2044.43  4907.9 2040.70  4913.2 2038.88  4939.6 2038.80
  4951.7 2030.48  4962.2 2026.32  4976.6 2024.93  4977.8 2023.80  4978.3 2023.30
  4988.8 2023.80  4993.8 2025.06  5067.1 2029.82  5098.5 2033.65  5119.4 2037.49
  5161.3 2038.72  5209.9 2042.65  5275.9 2043.97  5443.8 2045.47  5482.0 2049.38
  5519.9 2048.64  5552.6 2051.47  5558.9 2053.07  5579.8 2051.82  5601.1 2052.17
#Mann=7,-1,0
  4464.5   0.035       0  4539.1    0.07       0  4677.7   0.035       0
  4850.0    0.07       0  4977.8    0.07       0  4988.8    0.07       0
  5275.9   0.035       0
Bank Sta=4977.8,4988.8
Exp/Cntr=0.3,0.1