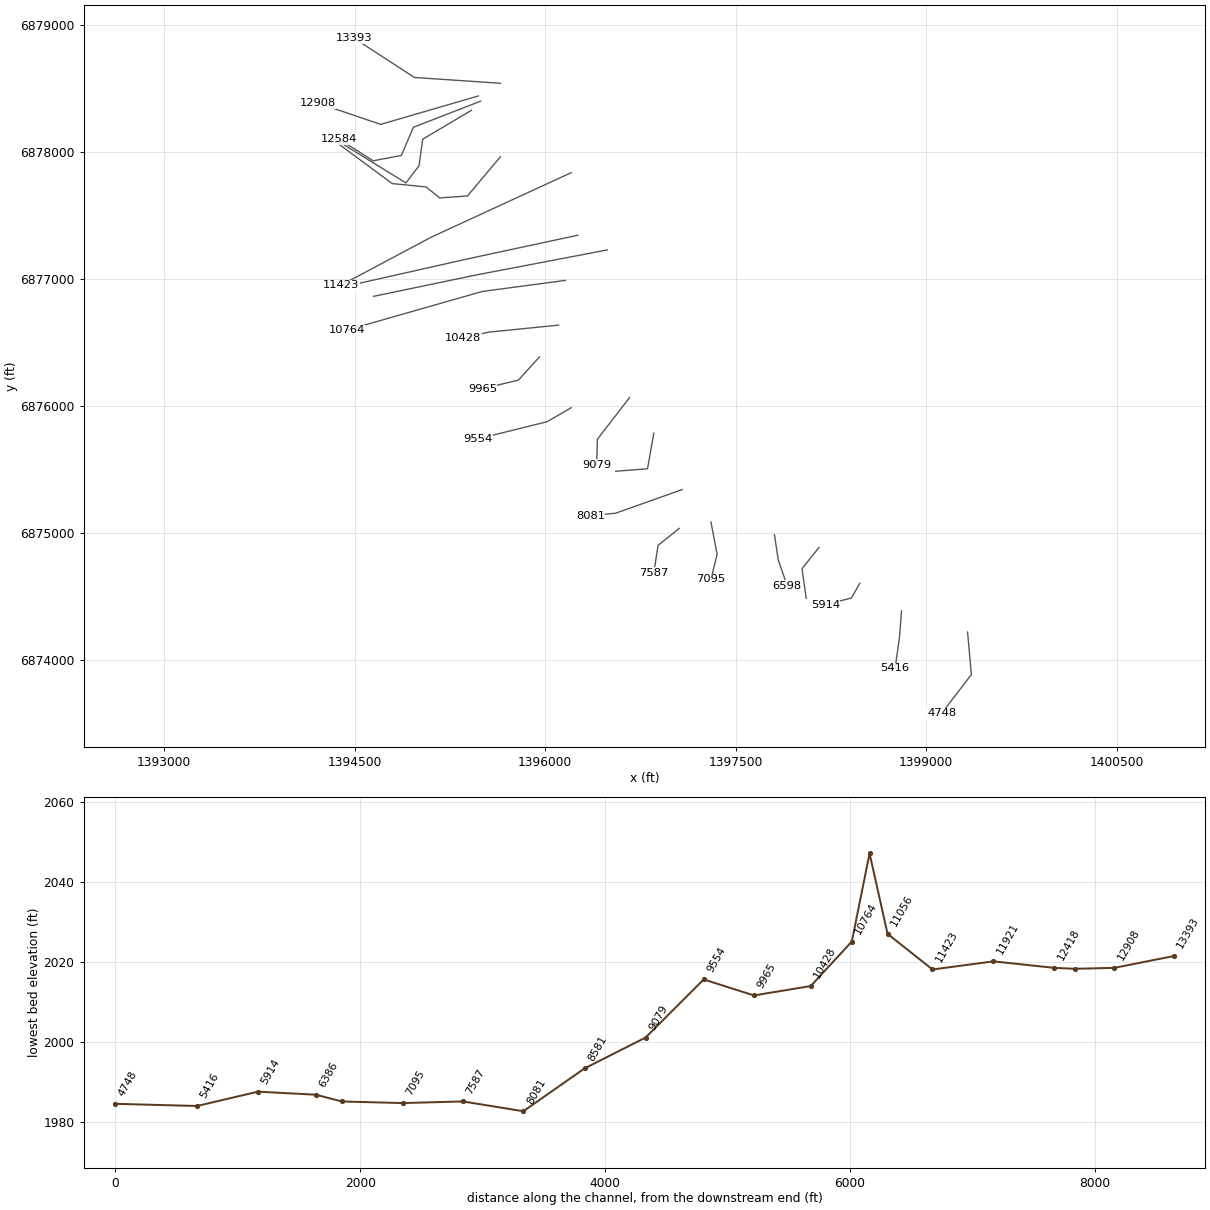
HEC-RAS study Rock Creek.prj: Rock Creek Base Level Engineering

--- Rock Creek.g01 (geometry) --- (continued)

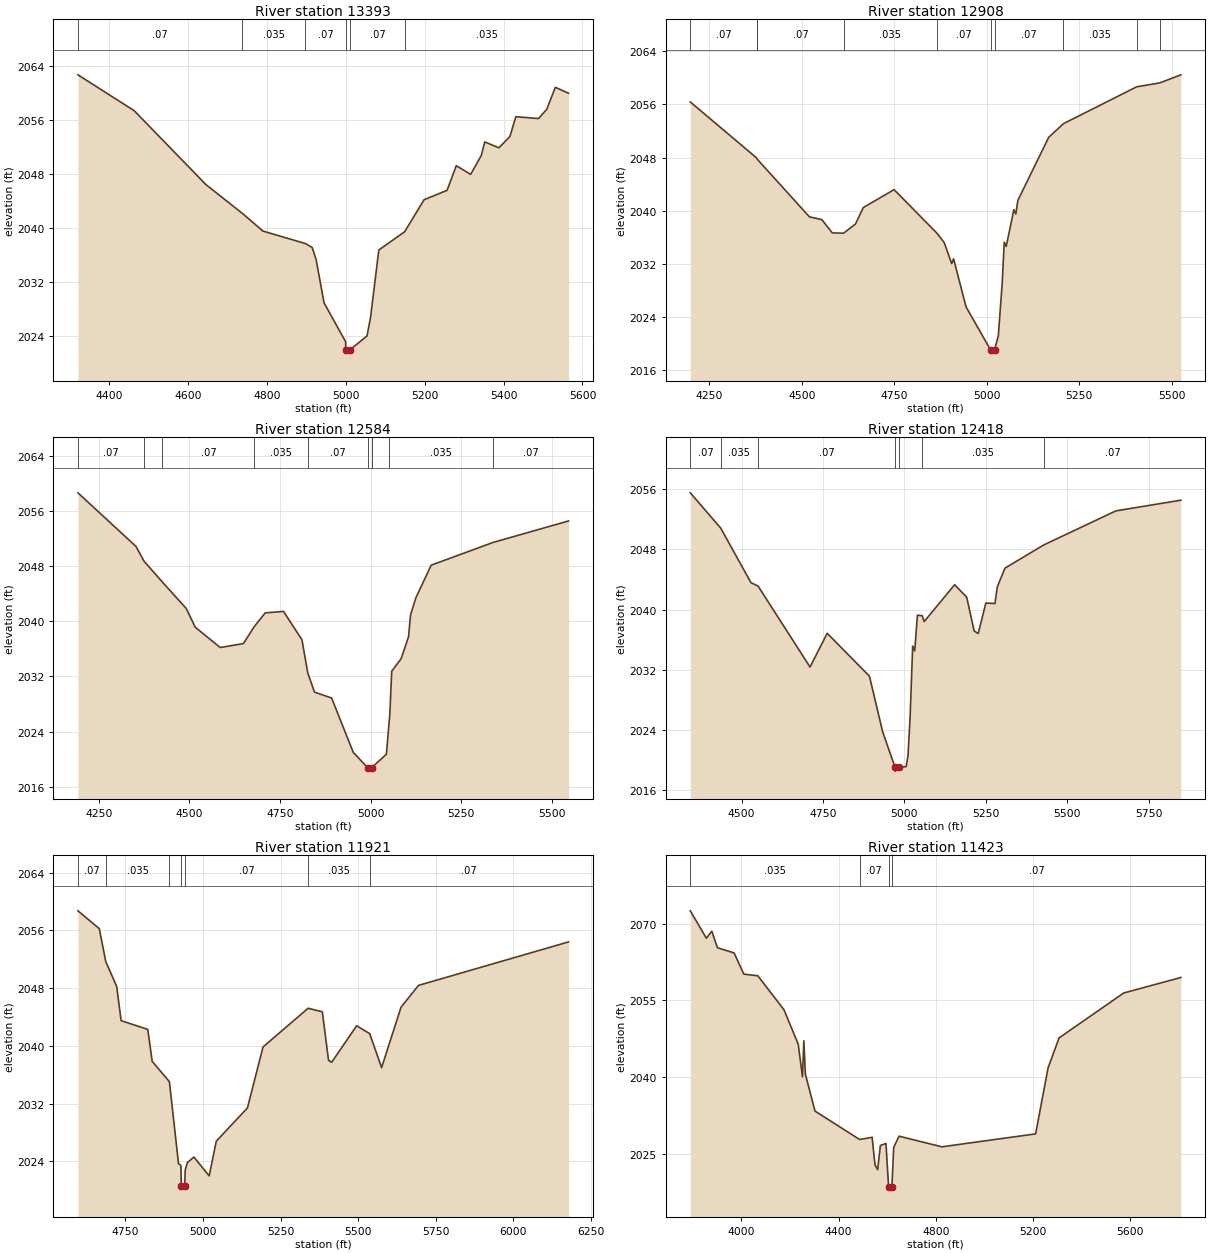
Type RM Length L Ch R = 1,13393,485,485,485
BEGIN DESCRIPTION:
Rock Creek 24.0
END DESCRIPTION:
XS GIS Cut Line= 3
      1395647.22      6878541.35      1394970.36      6878587.13
      1394497.02      6878895.08
#Sta/Elev= 30
  4321.6 2062.74  4464.1 2057.42  4646.0 2046.45  4738.3 2042.18  4790.3 2039.56
  4897.8 2037.71  4915.2 2037.12  4925.2 2035.31  4945.2 2028.91  5000.0 2023.13
  5000.1 2021.95  5000.6 2021.45  5011.1 2021.95  5054.1 2024.00  5062.9 2026.70
  5084.0 2036.75  5149.5 2039.46  5198.7 2044.21  5256.9 2045.60  5280.3 2049.26
  5316.6 2047.97  5343.6 2050.77  5352.4 2052.79  5388.2 2051.91  5416.1 2053.58
  5431.2 2056.53  5488.6 2056.25  5509.6 2057.63  5531.3 2060.89  5564.7 2060.01
#Mann=6,-1,0
  4321.6    0.07       0  4738.3   0.035       0  4897.8    0.07       0
  5000.1    0.07       0  5011.1    0.07       0  5149.5   0.035       0
Bank Sta=5000.1,5011.1
Exp/Cntr=0.3,0.1

Type RM Length L Ch R = 1,12908,324,324,324
BEGIN DESCRIPTION:
Rock Creek 23.0
END DESCRIPTION:
XS GIS Cut Line= 3
      1395473.57      6878441.52      1394704.54      6878217.84
      1394208.15      6878386.62
#Sta/Elev= 30
  4199.1 2056.38  4378.0 2047.95  4379.7 2047.76  4520.9 2039.06  4554.4 2038.64
  4582.7 2036.64  4613.1 2036.59  4645.4 2037.98  4666.3 2040.45  4749.6 2043.16
  4866.0 2036.56  4885.0 2035.17  4905.2 2032.01  4910.4 2032.72  4944.0 2025.48
  5010.1 2019.01  5010.6 2018.51  5021.2 2019.01  5031.2 2021.14  5041.8 2029.17
  5047.1 2035.25  5052.4 2034.59  5073.2 2040.14  5078.4 2039.47  5084.0 2041.55
  5167.3 2051.05  5206.9 2053.10  5404.7 2058.66  5467.7 2059.26  5524.3 2060.47
#Mann=10,-1,0
  4199.1    0.07       0  4378.0   0.035       0  4379.7    0.07       0
  4613.1   0.035       0  4866.0    0.07       0  5010.1    0.07       0
  5021.2    0.07       0  5206.9   0.035       0  5404.7    0.07       0
  5467.7   0.035       0
Bank Sta=5010.1,5021.2
Exp/Cntr=0.3,0.1

Type RM Length L Ch R = 1,12584,166,166,166
BEGIN DESCRIPTION:
Rock Creek 3995
END DESCRIPTION:
XS GIS Cut Line= 5
      1395490.97      6878400.30      1394962.14      6878195.07
      1394867.81      6877973.91      1394645.98      6877931.25
      1394375.48      6878102.99
#Sta/Elev= 30
  4192.3 2058.62  4352.5 2050.85  4374.7 2048.71  4425.6 2045.67  4491.3 2041.85
  4515.8 2039.15  4584.9 2036.19  4649.2 2036.77  4678.9 2039.22  4709.1 2041.21
  4759.6 2041.43  4810.6 2037.31  4826.6 2032.52  4845.1 2029.73  4892.4 2028.87
  4952.1 2021.00  4991.7 2018.77  4992.2 2018.27  5002.8 2018.77  5043.6 2020.72
  5050.6 2025.03  5053.2 2026.63  5058.3 2032.75  5084.3 2034.57  5104.7 2037.75
  5110.2 2040.90  5125.1 2043.42  5167.3 2048.13  5338.2 2051.43  5546.3 2054.54
#Mann=9,-1,0
  4192.3    0.07       0  4374.7   0.035       0  4425.6    0.07       0
  4678.9   0.035       0  4826.6    0.07       0  4991.7    0.07       0
  5002.8    0.07       0  5050.6   0.035       0  5338.2    0.07       0
Bank Sta=4991.7,5002.8
Exp/Cntr=0.3,0.1

Type RM Length L Ch R = 1,12418,497,497,497
BEGIN DESCRIPTION:
Rock Creek 22.0
END DESCRIPTION:
XS GIS Cut Line= 5
      1395419.34      6878328.69      1395035.80      6878101.34
      1395006.59      6877891.83      1394903.41      6877756.96
      1394325.21      6878113.50
#Sta/Elev= 30
  4342.6 2055.54  4436.1 2050.84  4529.0 2043.58  4550.6 2043.14  4710.3 2032.36
  4763.0 2036.85  4892.8 2031.14  4933.2 2023.76  4971.4 2019.01  4971.9 2018.51
  4982.5 2019.01  5005.4 2019.11  5011.0 2020.51  5017.4 2025.52  5025.5 2035.15
  5031.8 2034.51  5040.0 2039.26  5054.7 2039.19  5060.8 2038.41  5154.3 2043.31
  5191.4 2041.66  5214.2 2037.16  5226.7 2036.82  5250.2 2040.87  5278.1 2040.81
  5285.4 2043.03  5308.9 2045.52  5428.2 2048.61  5649.6 2053.14  5849.1 2054.56
#Mann=7,-1,0
  4342.6    0.07       0  4436.1   0.035       0  4550.6    0.07       0
  4971.4    0.07       0  4982.5    0.07       0  5054.7   0.035       0
  5428.2    0.07       0
Bank Sta=4971.4,4982.5
Exp/Cntr=0.3,0.1

Type RM Length L Ch R = 1,11921,498,498,498
BEGIN DESCRIPTION:
Rock Creek 21.0
END DESCRIPTION:
XS GIS Cut Line= 6
      1395646.83      6877962.51      1395388.23      6877654.60
      1395169.38      6877639.02      1395062.53      6877725.57
      1394795.44      6877752.06      1394351.69      6878080.19
#Sta/Elev= 30
  4597.9 2058.72  4666.6 2056.25  4687.5 2051.68  4722.6 2048.24  4736.9 2043.49
  4822.7 2042.28  4837.0 2037.84  4892.3 2035.03  4921.6 2023.70  4929.4 2023.38
  4930.4 2020.63  4930.9 2020.13  4941.5 2020.63  4943.3 2022.81  4950.2 2023.81
  4971.1 2024.58  5020.4 2021.97  5043.3 2026.78  5143.6 2031.39  5193.7 2039.84
  5338.8 2045.21  5384.6 2044.72  5404.7 2037.99  5414.7 2037.72  5495.1 2042.78
  5537.1 2041.69  5575.5 2036.98  5637.9 2045.35  5694.2 2048.38  6177.2 2054.41
#Mann=7,-1,0
  4597.9    0.07       0  4687.5   0.035       0  4892.3    0.07       0
  4930.4    0.07       0  4941.5    0.07       0  5338.8   0.035       0
  5537.1    0.07       0
Bank Sta=4930.4,4941.5
Exp/Cntr=0.3,0.1

Type RM Length L Ch R = 1,11423,367,367,367
BEGIN DESCRIPTION:
Rock Creek 20.0
END DESCRIPTION:
XS GIS Cut Line= 3
      1396204.96      6877837.98      1395106.21      6877331.89
      1394392.45      6876952.55
#Sta/Elev= 30
  3790.3 2072.50  3856.3 2067.15  3878.9 2068.51  3901.8 2065.29  3970.7 2064.26
  4010.4 2060.13  4068.1 2059.80  4175.6 2053.17  4234.3 2046.42  4251.8 2040.06
  4257.3 2047.11  4263.7 2040.59  4303.2 2033.36  4486.9 2027.80  4538.3 2028.23
  4549.9 2022.87  4560.9 2021.90  4572.3 2026.64  4595.2 2027.02  4605.9 2018.60
  4606.4 2018.10  4619.5 2018.60  4627.0 2026.26  4649.0 2028.45  4824.9 2026.37
  5210.8 2028.90  5261.8 2041.76  5307.1 2047.65  5573.1 2056.44  5808.3 2059.47
#Mann=4,-1,0
  3790.3   0.035       0  4486.9    0.07       0  4605.9    0.07       0
  4619.5    0.07       0
Bank Sta=4605.9,4619.5
Exp/Cntr=0.3,0.1

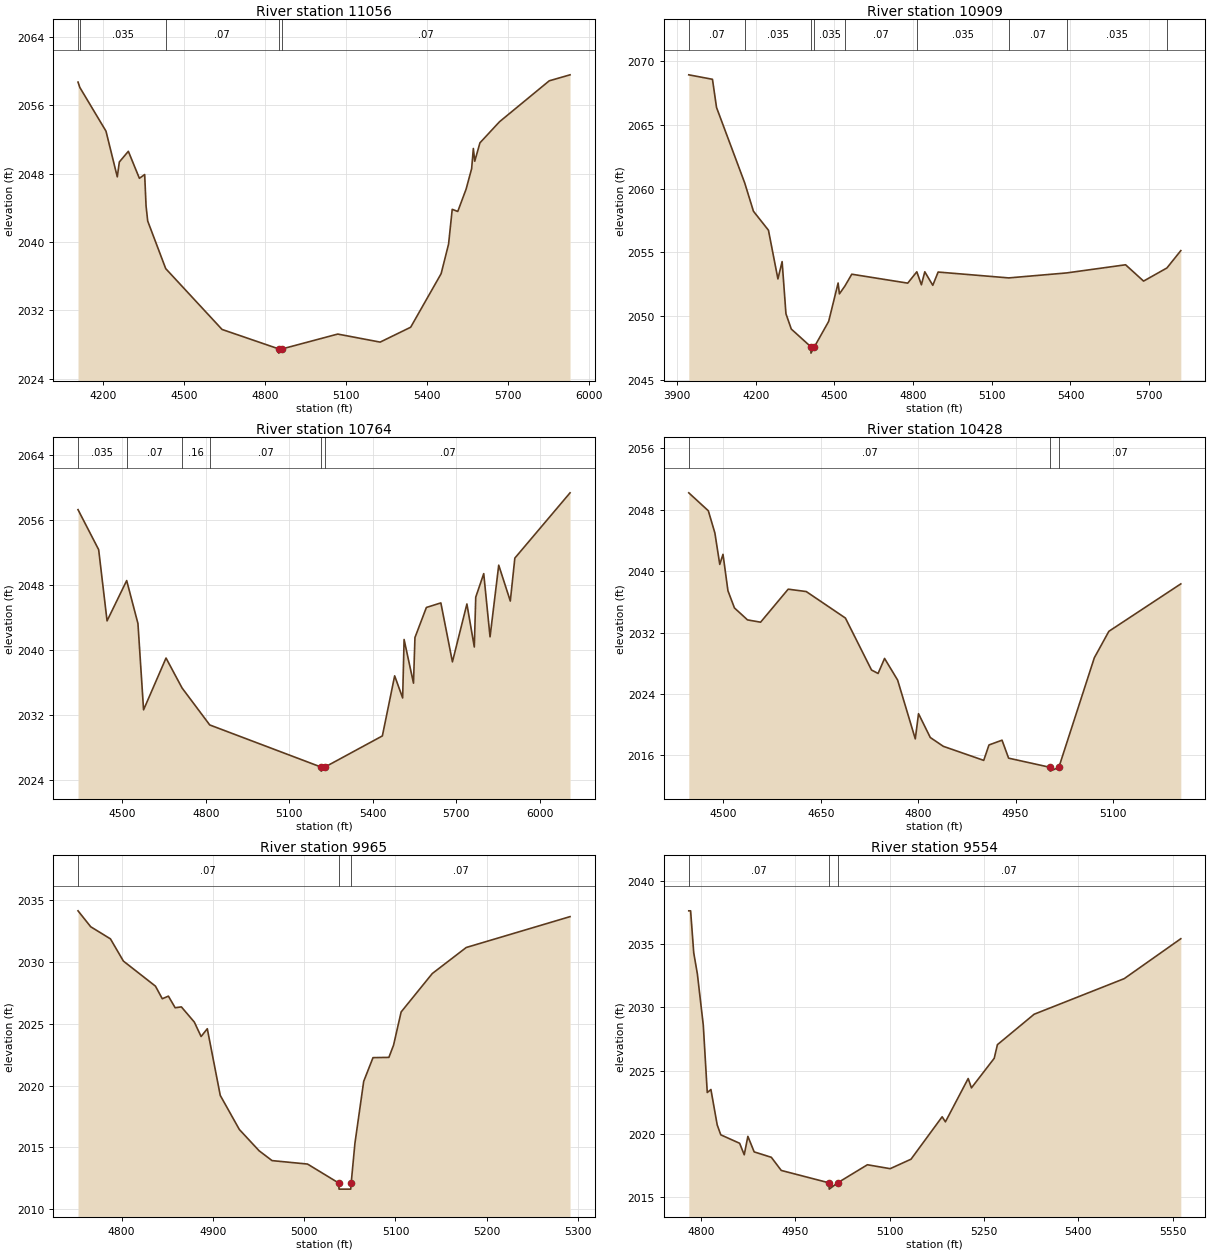
Type RM Length L Ch R = 1,11056,147,147,147
BEGIN DESCRIPTION:
Rock Creek 19.0
END DESCRIPTION:
XS GIS Cut Line= 3
      1396256.97      6877345.60      1395385.42      6877158.57
      1394479.97      6876954.74
#Sta/Elev= 30
  4108.6 2058.72  4115.4 2058.09  4212.0 2052.98  4253.8 2047.63  4261.4 2049.37
  4294.7 2050.62  4335.6 2047.46  4355.1 2047.90  4360.2 2044.23  4366.3 2042.46
  4432.9 2036.89  4641.3 2029.77  4850.4 2027.50  4850.9 2027.00  4864.1 2027.50
  5069.0 2029.23  5225.9 2028.29  5338.7 2030.03  5451.4 2036.30  5478.9 2039.76
  5492.4 2043.83  5512.9 2043.58  5543.7 2046.19  5564.2 2048.59  5570.5 2050.95
  5575.7 2049.46  5594.9 2051.61  5667.3 2054.08  5851.2 2058.87  5928.1 2059.57
#Mann=5,-1,0
  4108.6    0.07       0  4115.4   0.035       0  4432.9    0.07       0
  4850.4    0.07       0  4864.1    0.07       0
Bank Sta=4850.4,4864.1
Exp/Cntr=0.3,0.1

Type RM Length L Ch R = 1,10909,145,145,145
BEGIN DESCRIPTION:
Rock Creek 4286
END DESCRIPTION:
XS GIS Cut Line= 3
      1396488.88      6877229.90      1395452.32      6877031.89
      1394648.78      6876864.48
#Sta/Elev= 30
  3944.7 2068.93  4035.0 2068.58  4050.5 2066.37  4157.8 2060.46  4191.3 2058.23
  4248.5 2056.74  4284.6 2052.92  4300.6 2054.28  4315.2 2050.19  4335.5 2048.99
  4410.1 2047.60  4410.6 2047.10  4423.8 2047.60  4478.1 2049.59  4514.1 2052.60
  4519.1 2051.75  4540.2 2052.37  4566.2 2053.29  4779.6 2052.59  4814.2 2053.48
  4831.7 2052.46  4844.6 2053.48  4875.1 2052.42  4895.5 2053.46  5164.6 2053.00
  5385.0 2053.39  5610.2 2054.03  5678.8 2052.75  5767.8 2053.78  5820.8 2055.14
#Mann=9,-1,0
  3944.7    0.07       0  4157.8   0.035       0  4410.1   0.035       0
  4423.8   0.035       0  4540.2    0.07       0  4814.2   0.035       0
  5164.6    0.07       0  5385.0   0.035       0  5767.8    0.07       0
Bank Sta=4410.1,4423.8
Exp/Cntr=0.3,0.1

Type RM Length L Ch R = 1,10764,336,336,336
BEGIN DESCRIPTION:
Rock Creek 3991
END DESCRIPTION:
XS GIS Cut Line= 3
      1396158.50      6876989.95      1395505.16      6876903.06
      1394438.50      6876598.81
#Sta/Elev= 30
  4340.9 2057.24  4415.1 2052.32  4445.3 2043.56  4515.8 2048.52  4556.3 2043.23
  4576.5 2032.62  4657.2 2038.99  4714.8 2035.31  4814.3 2030.76  5214.5 2025.58
  5215.0 2025.08  5228.2 2025.58  5434.7 2029.41  5478.9 2036.80  5507.6 2034.08
  5512.8 2041.27  5546.6 2035.90  5551.8 2041.51  5592.9 2045.21  5644.9 2045.77
  5686.5 2038.52  5738.5 2045.64  5765.1 2040.35  5770.3 2046.48  5799.0 2049.37
  5821.7 2041.60  5852.9 2050.41  5894.5 2046.00  5910.8 2051.28  6109.2 2059.31
#Mann=6,-1,0
  4340.9   0.035       0  4515.8    0.07       0  4714.8    0.16       0
  4814.3    0.07       0  5214.5    0.07       0  5228.2    0.07       0
Bank Sta=5214.5,5228.2
Exp/Cntr=0.3,0.1

Type RM Length L Ch R = 1,10428,463,463,463
BEGIN DESCRIPTION:
Rock Creek 18.0
END DESCRIPTION:
XS GIS Cut Line= 3
      1396105.00      6876638.00      1395554.56      6876582.82
      1395355.03      6876538.01
#Sta/Elev= 30
  4446.8 2050.21  4476.9 2047.87  4487.0 2044.98  4494.5 2040.89  4499.5 2042.20
  4507.1 2037.46  4517.1 2035.22  4537.2 2033.66  4557.4 2033.36  4599.9 2037.66
  4627.7 2037.35  4688.0 2033.90  4728.2 2027.13  4738.3 2026.68  4748.3 2028.64
  4768.4 2025.82  4795.6 2018.16  4800.6 2021.44  4818.7 2018.34  4838.8 2017.19
  4901.0 2015.36  4909.1 2017.37  4929.2 2017.99  4939.3 2015.65  5002.9 2014.46
  5003.4 2013.96  5016.7 2014.46  5071.3 2028.72  5093.7 2032.17  5204.5 2038.35
#Mann=3,-1,0
  4446.8    0.07       0  5002.9    0.07       0  5016.7    0.07       0
Bank Sta=5002.9,5016.7
Exp/Cntr=0.3,0.1

Type RM Length L Ch R = 1,9965,411,411,411
BEGIN DESCRIPTION:
Rock Creek 17.0
END DESCRIPTION:
XS GIS Cut Line= 3
      1395955.01      6876388.01      1395788.42      6876204.70
      1395504.97      6876137.99
#Sta/Elev= 30
  4752.3 2034.16  4766.2 2032.87  4787.8 2031.89  4802.0 2030.09  4837.1 2028.06
  4844.6 2027.04  4851.3 2027.25  4858.7 2026.31  4865.5 2026.38  4879.7 2025.15
  4887.1 2023.98  4893.9 2024.61  4908.1 2019.21  4929.0 2016.45  4950.6 2014.73
  4964.8 2013.93  5003.7 2013.65  5037.7 2012.12  5038.2 2011.62  5051.0 2011.62
  5051.5 2012.12  5055.6 2015.34  5065.2 2020.35  5075.4 2022.27  5092.8 2022.29
  5097.9 2023.28  5106.2 2025.97  5140.3 2029.08  5177.5 2031.19  5291.2 2033.69
#Mann=3,-1,0
  4752.3    0.07       0  5037.7    0.07       0  5051.5    0.07       0
Bank Sta=5037.7,5051.5
Exp/Cntr=0.3,0.1

Type RM Length L Ch R = 1,9554,475,475,475
BEGIN DESCRIPTION:
Rock Creek 16.0
END DESCRIPTION:
XS GIS Cut Line= 3
      1396205.00      6875988.00      1396014.86      6875877.92
      1395468.53      6875742.34
#Sta/Elev= 30
  4780.3 2037.65  4783.2 2037.65  4788.2 2034.32  4794.0 2032.64  4803.4 2028.58
  4809.7 2023.26  4815.5 2023.50  4825.5 2020.70  4831.2 2019.91  4861.2 2019.24
  4868.5 2018.33  4874.3 2019.79  4884.3 2018.56  4911.6 2018.13  4927.4 2017.09
  5003.2 2016.11  5003.7 2015.61  5017.1 2016.11  5064.4 2017.54  5100.6 2017.23
  5133.8 2017.98  5183.3 2021.34  5188.5 2020.94  5224.7 2024.37  5229.9 2023.63
  5266.1 2025.97  5271.2 2027.05  5329.6 2029.46  5472.9 2032.28  5562.9 2035.44
#Mann=3,-1,0
  4780.3    0.07       0  5003.2    0.07       0  5017.1    0.07       0
Bank Sta=5003.2,5017.1
Exp/Cntr=0.3,0.1

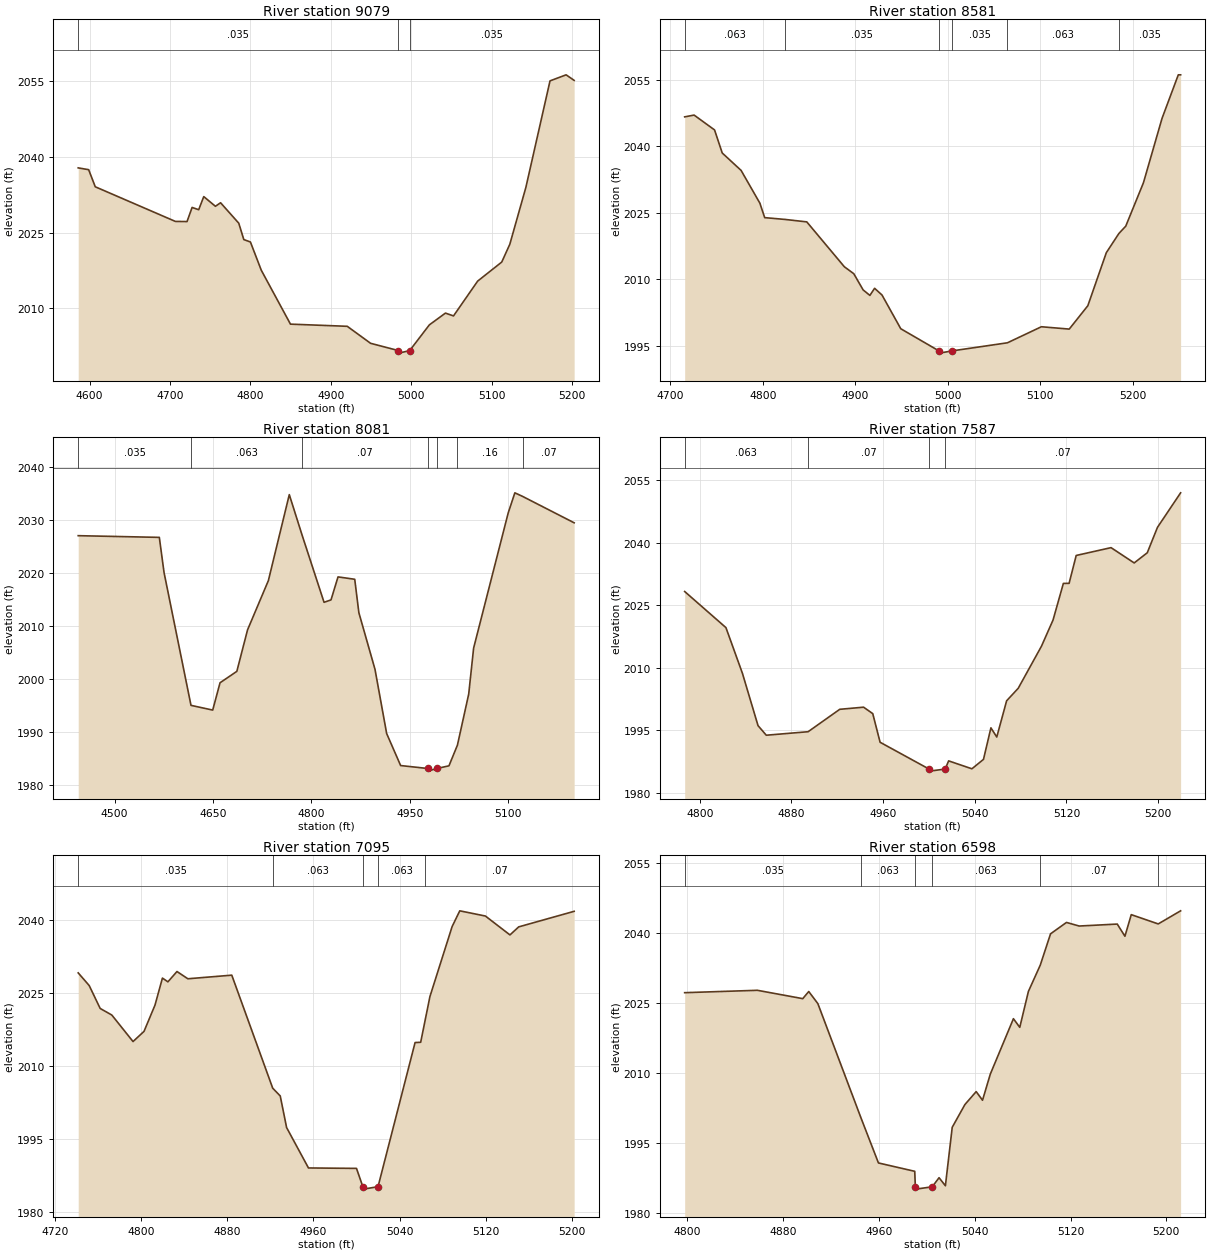
Type RM Length L Ch R = 1,9079,498,498,498
BEGIN DESCRIPTION:
Rock Creek 15.0
END DESCRIPTION:
XS GIS Cut Line= 3
      1396664.31      6876068.04      1396410.97      6875740.35
      1396405.00      6875538.04
#Sta/Elev= 30
  4585.8 2037.84  4598.8 2037.48  4607.0 2034.09  4706.6 2027.22  4721.1 2027.19
  4727.4 2029.99  4735.6 2029.54  4741.9 2032.14  4756.4 2030.22  4762.8 2030.92
  4785.4 2026.87  4791.7 2023.62  4799.9 2023.14  4813.4 2017.54  4849.7 2006.84
  4920.3 2006.41  4949.3 2003.04  4984.0 2001.59  4984.5 2001.09  4997.9 2001.59
  5022.4 2006.70  5042.4 2009.03  5052.4 2008.47  5082.4 2015.37  5112.4 2019.16
  5122.4 2022.68  5142.4 2033.98  5172.4 2055.10  5192.4 2056.30  5202.4 2055.20
#Mann=3,-1,0
  4585.8   0.035       0  4984.0   0.035       0  4997.9   0.035       0
Bank Sta=4984,4997.9
Exp/Cntr=0.3,0.1

Type RM Length L Ch R = 1,8581,500,500,500
BEGIN DESCRIPTION:
Rock Creek 14.0
END DESCRIPTION:
XS GIS Cut Line= 3
      1396855.01      6875788.04      1396805.79      6875507.83
      1396554.97      6875488.00
#Sta/Elev= 30
  4715.5 2046.68  4725.7 2047.08  4747.8 2043.73  4756.1 2038.53  4776.5 2034.60
  4796.8 2027.21  4802.0 2023.95  4823.7 2023.55  4847.5 2022.99  4888.1 2012.87
  4898.3 2011.30  4908.4 2007.65  4915.7 2006.41  4920.8 2008.01  4928.8 2006.50
  4949.1 1998.89  4990.4 1993.89  4990.9 1993.39  5004.4 1993.89  5064.4 1995.72
  5101.1 1999.34  5131.2 1998.81  5151.3 2004.08  5171.3 2016.05  5184.9 2020.38
  5192.3 2022.03  5211.4 2031.81  5231.5 2046.33  5249.1 2056.16  5251.6 2056.16
#Mann=6,-1,0
  4715.5   0.063       0  4823.7   0.035       0  4990.4   0.035       0
  5004.4   0.035       0  5064.4   0.063       0  5184.9   0.035       0
Bank Sta=4990.4,5004.4
Exp/Cntr=0.3,0.1

Type RM Length L Ch R = 1,8081,494,494,494
BEGIN DESCRIPTION:
Rock Creek 13.0
END DESCRIPTION:
XS GIS Cut Line= 3
      1397078.32      6875343.79      1396554.93      6875157.96
      1396355.03      6875138.00
#Sta/Elev= 30
  4444.6 2027.08  4568.3 2026.76  4575.5 2020.13  4616.6 1995.09  4649.7 1994.20
  4660.9 1999.35  4686.5 2001.50  4702.8 2009.31  4734.6 2018.61  4766.5 2034.82
  4785.8 2027.27  4819.5 2014.52  4830.1 2014.97  4840.8 2019.31  4866.3 2018.86
  4872.6 2012.56  4897.2 2001.88  4915.0 1989.77  4936.3 1983.74  4977.5 1983.19
  4978.0 1982.69  4991.5 1983.19  5010.0 1983.69  5022.9 1987.59  5040.1 1997.21
  5047.6 2005.89  5100.4 2031.40  5110.5 2035.16  5122.2 2034.49  5200.9 2029.51
#Mann=7,-1,0
  4444.6   0.035       0  4616.6   0.063       0  4785.8    0.07       0
  4977.5    0.07       0  4991.5    0.07       0  5022.9    0.16       0
  5122.2    0.07       0
Bank Sta=4977.5,4991.5
Exp/Cntr=0.3,0.1

Type RM Length L Ch R = 1,7587,492,492,492
BEGIN DESCRIPTION:
Rock Creek 12.0
END DESCRIPTION:
XS GIS Cut Line= 3
      1397055.00      6875038.00      1396888.48      6874905.02
      1396855.00      6874687.99
#Sta/Elev= 30
  4786.9 2028.26  4822.9 2019.59  4837.3 2008.61  4850.9 1996.06  4858.1 1993.76
  4894.6 1994.60  4922.2 1999.98  4943.0 2000.49  4951.0 1998.94  4957.4 1992.07
  5000.1 1985.64  5000.6 1985.14  5014.2 1985.64  5017.2 1987.60  5037.5 1985.70
  5047.6 1987.96  5054.1 1995.53  5059.2 1993.33  5067.8 2002.03  5077.9 2005.02
  5098.2 2015.13  5108.3 2021.42  5117.3 2030.20  5122.3 2030.22  5128.5 2036.91
  5158.9 2038.79  5179.1 2035.12  5190.5 2037.56  5199.4 2043.66  5219.6 2051.95
#Mann=4,-1,0
  4786.9   0.063       0  4894.6    0.07       0  5000.1    0.07       0
  5014.2    0.07       0
Bank Sta=5000.1,5014.2
Exp/Cntr=0.3,0.1

Type RM Length L Ch R = 1,7095,497,497,497
BEGIN DESCRIPTION:
Rock Creek 11.0
END DESCRIPTION:
XS GIS Cut Line= 3
      1397304.99      6875088.04      1397353.43      6874834.22
      1397305.00      6874638.01
#Sta/Elev= 30
  4741.6 2029.16  4751.8 2026.56  4762.0 2021.85  4772.8 2020.50  4792.5 2015.05
  4802.7 2017.14  4812.9 2022.54  4819.8 2028.09  4824.9 2027.32  4833.3 2029.44
  4843.4 2027.95  4884.2 2028.69  4922.2 2005.47  4929.2 2003.87  4935.1 1997.38
  4955.4 1989.08  5000.0 1988.99  5005.9 1985.23  5006.4 1984.73  5020.0 1985.23
  5054.4 2014.85  5059.6 2014.90  5063.5 2019.17  5068.2 2024.31  5088.8 2038.68
  5095.9 2041.91  5119.7 2040.84  5142.5 2036.96  5150.6 2038.61  5202.1 2041.81
#Mann=5,-1,0
  4741.6   0.035       0  4922.2   0.063       0  5005.9   0.063       0
  5020.0   0.063       0  5063.5    0.07       0
Bank Sta=5005.9,5020
Exp/Cntr=0.3,0.1

Type RM Length L Ch R = 1,6598,212,212,212
BEGIN DESCRIPTION:
Rock Creek 10.0
END DESCRIPTION:
XS GIS Cut Line= 3
      1397805.00      6874987.99      1397835.01      6874788.03
      1397904.99      6874588.02
#Sta/Elev= 30
  4797.8 2027.25  4858.5 2027.76  4896.4 2025.97  4901.4 2027.50  4909.0 2024.91
  4945.0 2000.41  4959.6 1990.74  4989.9 1988.95  4990.4 1985.63  4990.9 1985.13
  5004.5 1985.63  5010.2 1987.58  5015.5 1985.85  5021.2 1998.39  5031.8 2003.27
  5041.2 2006.04  5046.5 2004.19  5053.0 2009.79  5072.3 2021.67  5077.6 2019.82
  5084.8 2027.51  5094.7 2033.15  5103.3 2039.87  5116.6 2042.31  5127.2 2041.54
  5159.0 2041.96  5165.4 2039.35  5170.7 2043.98  5193.2 2041.99  5211.9 2044.80
#Mann=6,-1,0
  4797.8   0.035       0  4945.0   0.063       0  4990.4   0.063       0
  5004.5   0.063       0  5094.7    0.07       0  5193.2    0.16       0
Bank Sta=4990.4,5004.5
Exp/Cntr=0.3,0.1

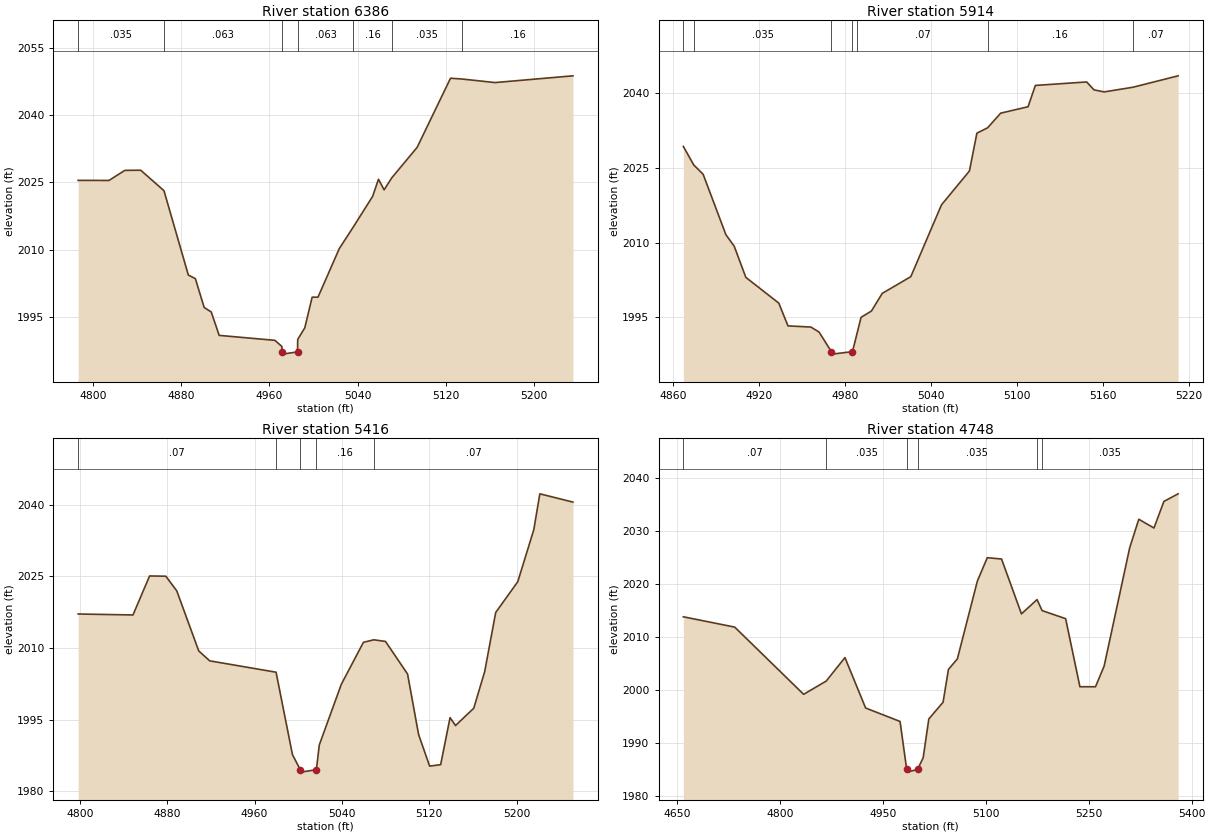
Type RM Length L Ch R = 1,6386,472,472,472
BEGIN DESCRIPTION:
Rock Creek 9.0
END DESCRIPTION:
XS GIS Cut Line= 3
      1398154.98      6874887.98      1398021.59      6874721.15
      1398055.00      6874488.03
#Sta/Elev= 30
  4786.4 2025.47  4814.4 2025.46  4828.8 2027.70  4843.2 2027.73  4864.3 2023.18
  4886.4 2004.42  4892.8 2003.61  4900.8 1997.19  4907.2 1996.20  4914.4 1990.99
  4964.9 1989.89  4971.3 1988.54  4971.4 1987.32  4971.9 1986.82  4985.5 1987.32
  4985.7 1990.10  4992.1 1992.66  4998.8 1999.49  5004.1 1999.49  5023.4 2010.28
  5036.3 2015.16  5053.7 2021.92  5059.0 2025.72  5064.1 2023.37  5071.1 2026.05
  5094.1 2032.82  5124.4 2048.20  5134.8 2048.02  5164.8 2047.23  5235.5 2048.73
#Mann=7,-1,0
  4786.4   0.035       0  4864.3   0.063       0  4971.4   0.063       0
  4985.5   0.063       0  5036.3    0.16       0  5071.1   0.035       0
  5134.8    0.16       0
Bank Sta=4971.4,4985.5
Exp/Cntr=0.3,0.1

Type RM Length L Ch R = 1,5914,498,498,498
BEGIN DESCRIPTION:
Rock Creek 8.0
END DESCRIPTION:
XS GIS Cut Line= 3
      1398476.25      6874606.01      1398411.05      6874490.54
      1398205.05      6874438.01
#Sta/Elev= 30
  4867.4 2029.31  4874.7 2025.57  4881.2 2023.72  4897.1 2011.57  4902.9 2009.26
  4911.0 2003.00  4934.0 1997.83  4940.4 1993.25  4956.4 1993.02  4962.1 1992.01
  4970.7 1988.08  4971.2 1987.58  4985.4 1988.08  4988.9 1992.10  4991.4 1994.97
  4998.6 1996.23  5006.2 1999.79  5026.1 2003.14  5047.5 2017.57  5067.0 2024.37
  5072.2 2031.97  5079.7 2033.05  5088.8 2035.99  5107.9 2037.28  5113.0 2041.56
  5148.8 2042.26  5153.9 2040.67  5161.0 2040.26  5181.1 2041.20  5212.6 2043.49
#Mann=7,-1,0
  4867.4   0.063       0  4874.7   0.035       0  4970.7    0.07       0
  4985.4   0.035       0  4988.9    0.07       0  5079.7    0.16       0
  5181.1    0.07       0
Bank Sta=4970.7,4985.4
Exp/Cntr=0.3,0.1

Type RM Length L Ch R = 1,5416,668,668,668
BEGIN DESCRIPTION:
Rock Creek 7.0
END DESCRIPTION:
XS GIS Cut Line= 3
      1398805.00      6874388.04      1398789.64      6874187.12
      1398755.00      6873938.02
#Sta/Elev= 30
  4798.5 2017.09  4848.7 2016.89  4863.9 2025.05  4878.8 2025.00  4888.8 2021.93
  4908.9 2009.37  4918.9 2007.29  4979.7 2004.91  4994.7 1987.67  5001.9 1984.50
  5002.4 1984.00  5016.6 1984.50  5019.3 1989.70  5039.5 2002.41  5059.7 2011.17
  5069.2 2011.69  5079.9 2011.35  5100.1 2004.53  5110.2 1991.87  5120.3 1985.26
  5130.4 1985.56  5139.0 1995.40  5144.0 1993.75  5160.7 1997.37  5170.7 2005.03
  5180.8 2017.41  5201.0 2023.85  5215.7 2034.76  5221.2 2042.24  5251.5 2040.51
#Mann=5,-1,0
  4798.5    0.07       0  4979.7    0.16       0  5001.9    0.07       0
  5016.6    0.16       0  5069.2    0.07       0
Bank Sta=5001.9,5016.6
Exp/Cntr=0.3,0.1

Type RM Length L Ch R = 1,4748,400,400,400
BEGIN DESCRIPTION:
Rock Creek 6.0
END DESCRIPTION:
XS GIS Cut Line= 3
      1399325.10      6874222.59      1399355.00      6873888.00
      1399120.55      6873582.52
#Sta/Elev= 30
  4659.3 2013.85  4734.2 2011.90  4834.6 1999.22  4867.5 2001.72  4894.8 2006.15
  4924.9 1996.64  4975.1 1994.10  4984.8 1985.04  4985.3 1984.54  5000.6 1985.04
  5008.8 1987.26  5017.0 1994.57  5037.8 1997.73  5045.6 2003.92  5058.6 2005.90
  5087.7 2020.56  5102.2 2025.00  5123.0 2024.75  5152.0 2014.40  5174.7 2017.09
  5182.1 2015.02  5216.4 2013.49  5237.2 2000.65  5259.9 2000.65  5272.5 2004.55
  5309.8 2026.91  5323.0 2032.25  5345.1 2030.60  5359.6 2035.62  5380.3 2037.05
#Mann=6,-1,0
  4659.3    0.07       0  4867.5   0.035       0  4984.8   0.035       0
  5000.6   0.035       0  5174.7    0.16       0  5182.1   0.035       0
Bank Sta=4984.8,5000.6
Exp/Cntr=0.3,0.1