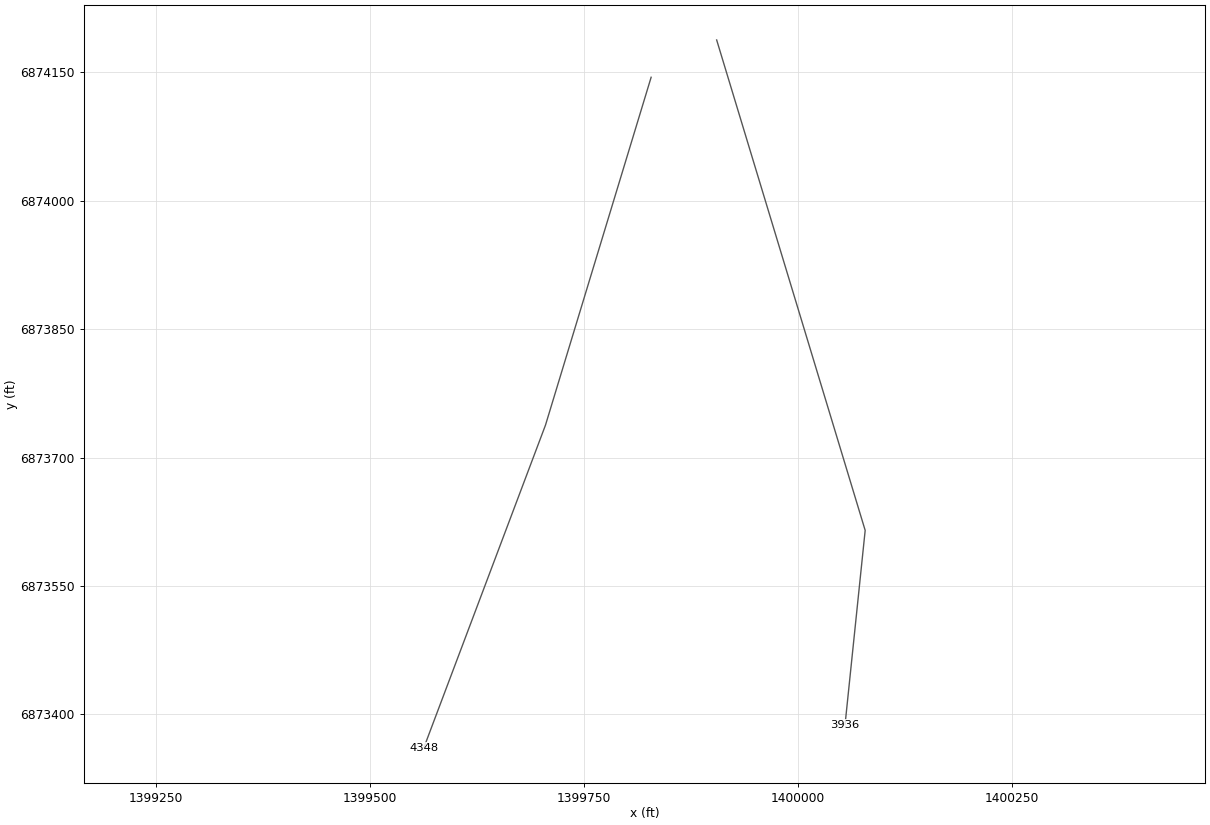
HEC-RAS study Rock Creek.prj: Rock Creek Base Level Engineering

--- Rock Creek.g01 (geometry) --- (continued)

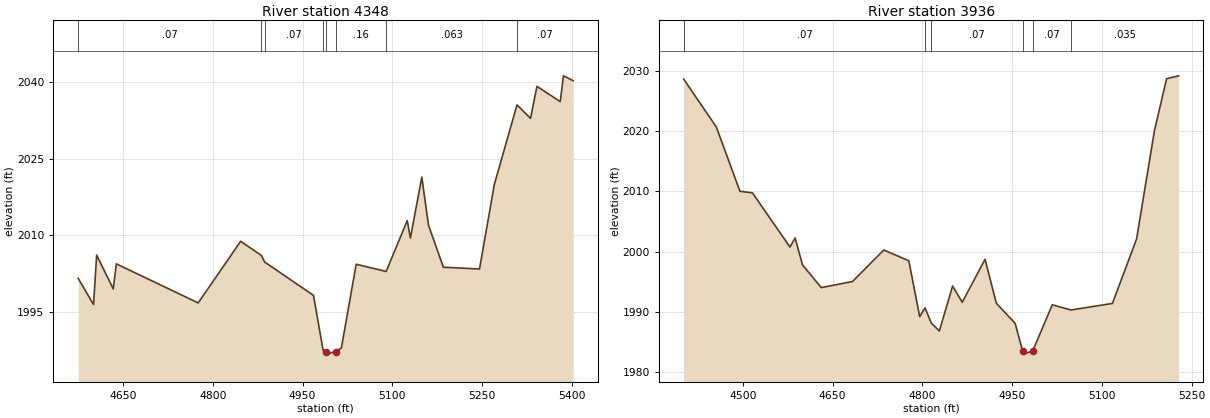
Type RM Length L Ch R = 1,4348,412,412,412
BEGIN DESCRIPTION:
Rock Creek 5.0
END DESCRIPTION:
XS GIS Cut Line= 3
      1399828.44      6874144.43      1399705.00      6873738.00
      1399562.95      6873361.25
#Sta/Elev= 30
  4574.9 2001.60  4600.6 1996.45  4605.8 2006.14  4633.5 1999.53  4638.7 2004.43
  4775.5 1996.78  4846.5 2008.85  4881.1 2006.08  4886.6 2004.79  4968.3 1998.25
  4984.3 1987.49  4988.7 1987.25  4989.2 1986.75  5005.4 1987.25  5014.8 1987.93
  5039.6 2004.35  5089.7 2002.94  5124.9 2012.90  5130.2 2009.48  5149.3 2021.42
  5160.4 2012.03  5185.3 2003.77  5245.7 2003.42  5270.6 2020.02  5308.4 2035.56
  5331.0 2032.92  5341.7 2039.19  5380.7 2036.20  5386.0 2041.25  5402.3 2040.30
#Mann=8,-1,0
  4574.9    0.07       0  4881.1    0.16       0  4886.6    0.07       0
  4984.3    0.16       0  4988.7    0.07       0  5005.4    0.16       0
  5089.7   0.063       0  5308.4    0.07       0
Bank Sta=4988.7,5005.4
Exp/Cntr=0.3,0.1

Type RM Length L Ch R = 1,3936,0,0,0
BEGIN DESCRIPTION:
Rock Creek 311
END DESCRIPTION:
XS GIS Cut Line= 3
      1399905.00      6874188.01      1400078.52      6873615.01
      1400055.00      6873388.03
#Sta/Elev= 30
  4401.3 2028.60  4455.9 2020.66  4495.4 2010.00  4516.2 2009.75  4578.9 2000.77
  4587.6 2002.27  4599.8 1997.83  4631.2 1994.05  4683.4 1995.06  4735.7 2000.28
  4777.5 1998.49  4795.6 1989.25  4804.5 1990.69  4815.0 1988.19  4828.5 1986.86
  4850.6 1994.31  4866.7 1991.62  4904.8 1998.74  4923.7 1991.45  4955.1 1988.13
  4967.6 1983.53  4968.1 1983.03  4984.3 1983.53  5017.1 1991.20  5048.4 1990.34
  5117.6 1991.43  5157.9 2002.09  5188.0 2020.16  5208.1 2028.65  5228.2 2029.13
#Mann=6,-1,0
  4401.3    0.07       0  4804.5    0.16       0  4815.0    0.07       0
  4967.6    0.07       0  4984.3    0.07       0  5048.4   0.035       0
Bank Sta=4967.6,4984.3
Exp/Cntr=0.3,0.1

Chan Stop Cuts=-1