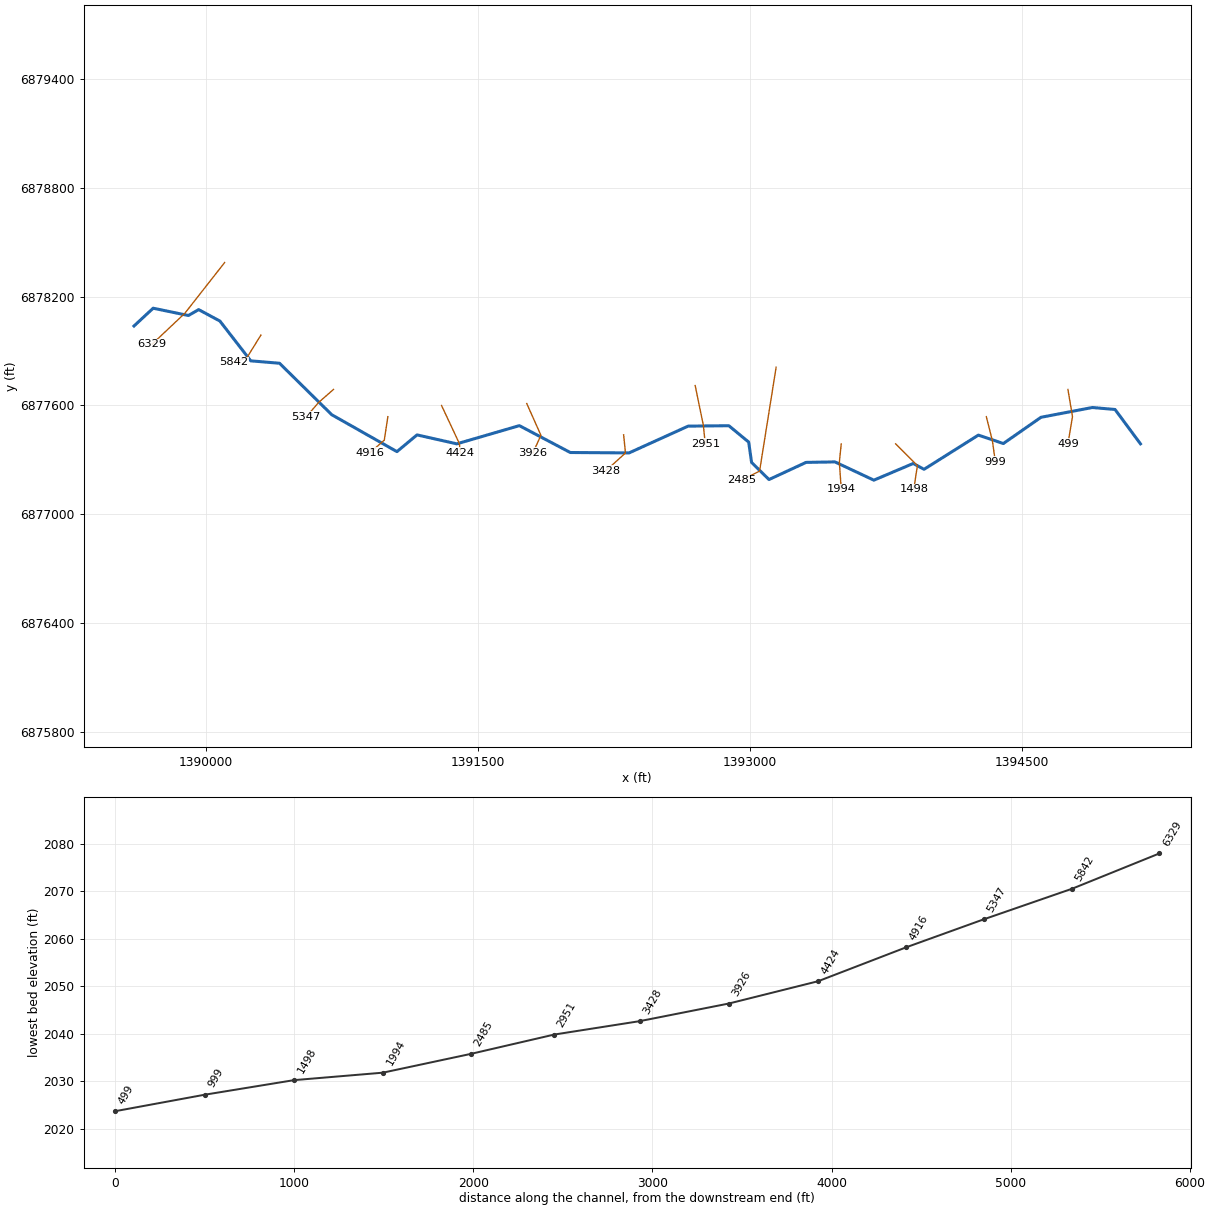
--- Rock Creek Trib1.prj (project) ---

Proj Title=Rock Creek Trib1 Base Level Engineering
Current Plan=p01
Default Exp/Contr=0.3,0.1
English Units
Geom File=g01
Flow File=f01
Plan File=p01
Y Axis Title=Elevation
X Axis Title(PF)=Main Channel Distance
X Axis Title(XS)=Station
BEGIN DESCRIPTION:
Rock Creek Trib1
END DESCRIPTION:
DSS Export Rating Curves= 0
DSS Export Rating Curve Sorted= 0
DSS Export Volume Flow Curves= 0
DXF OffsetX= 0
DXF OffsetY= 0
DXF ScaleX= 1
DXF ScaleY= 10

--- Rock Creek Trib1.p01 (plan) ---

Plan Title=Multiple Run
Short Identifier=Multiple
Geom File=g01
Flow File=f01
Subcritical Flow
K Sum by GR= 0
Std Step Tol= 0.01
Critical Tol= 0.01
Num of Std Step Trials= 20
Max Error Tol= 0.3
Flow Tol Ratio= 0.001
Split Flow NTrial= 30
Split Flow Tol= 0.02
Split Flow Ratio= 0.02
Log Output Level= 0
Friction Slope Method= 1
Unsteady Friction Slope Method= 2
Unsteady Bridges Friction Slope Method= 1
Parabolic Critical Depth
Global Vel Dist=  1 , 1 , 1
Global Log Level= 0
CheckData=True
Encroach Param= -1, 0, 0, 0
BEGIN DESCRIPTION:
Multiple Run
END DESCRIPTION:

--- Rock Creek Trib1.f01 (steady flow) ---

Flow Title=Multiple
Number of Profiles=7
Profile Names=10-year,25-year,50-year,1pct_min,100-year,1pct_plu,500-year
River Rch & RM= Rock Creek Trib1,Reach-1,6329
     326     467     587     367     733    1463    1157
River Rch & RM= Rock Creek Trib1,Reach-1,3428
     365     525     662     414     827    1650    1308
Boundary for River Rch & Prof#=Rock Creek Trib1,Reach-1,1
Up Type=0
Dn Type=3
Dn Slope=0.005
Boundary for River Rch & Prof#=Rock Creek Trib1,Reach-1,2
Up Type=0
Dn Type=3
Dn Slope=0.005
Boundary for River Rch & Prof#=Rock Creek Trib1,Reach-1,3
Up Type=0
Dn Type=3
Dn Slope=0.005
Boundary for River Rch & Prof#=Rock Creek Trib1,Reach-1,4
Up Type=0
Dn Type=3
Dn Slope=0.005
Boundary for River Rch & Prof#=Rock Creek Trib1,Reach-1,5
Up Type=0
Dn Type=3
Dn Slope=0.005
Boundary for River Rch & Prof#=Rock Creek Trib1,Reach-1,6
Up Type=0
Dn Type=3
Dn Slope=0.005
Boundary for River Rch & Prof#=Rock Creek Trib1,Reach-1,7
Up Type=0
Dn Type=3
Dn Slope=0.005

--- Rock Creek Trib1.g01 (geometry) ---

Geom Title=Existing Conditions

River Reach=Rock Creek Trib1,Reach-1
Reach XY= 30
      1389605.00      6878038.00      1389710.84      6878135.99
      1389905.10      6878095.80      1389961.55      6878128.42
      1390078.84      6878065.15      1390248.81      6877845.82
      1390407.45      6877832.53      1390695.32      6877548.76
      1391055.00      6877345.10      1391165.62      6877437.39
      1391384.96      6877388.05      1391730.00      6877488.41
      1392010.93      6877340.24      1392334.97      6877338.06
      1392660.94      6877485.74      1392885.02      6877488.04
      1392994.49      6877397.81      1393010.52      6877285.56
      1393106.62      6877191.12      1393310.93      6877285.76
      1393470.18      6877288.44      1393684.82      6877187.71
      1393901.78      6877279.72      1393961.55      6877247.58
      1394261.11      6877436.20      1394398.89      6877389.80
      1394606.47      6877534.45      1394889.84      6877588.47
      1395014.80      6877577.53      1395155.00      6877388.00

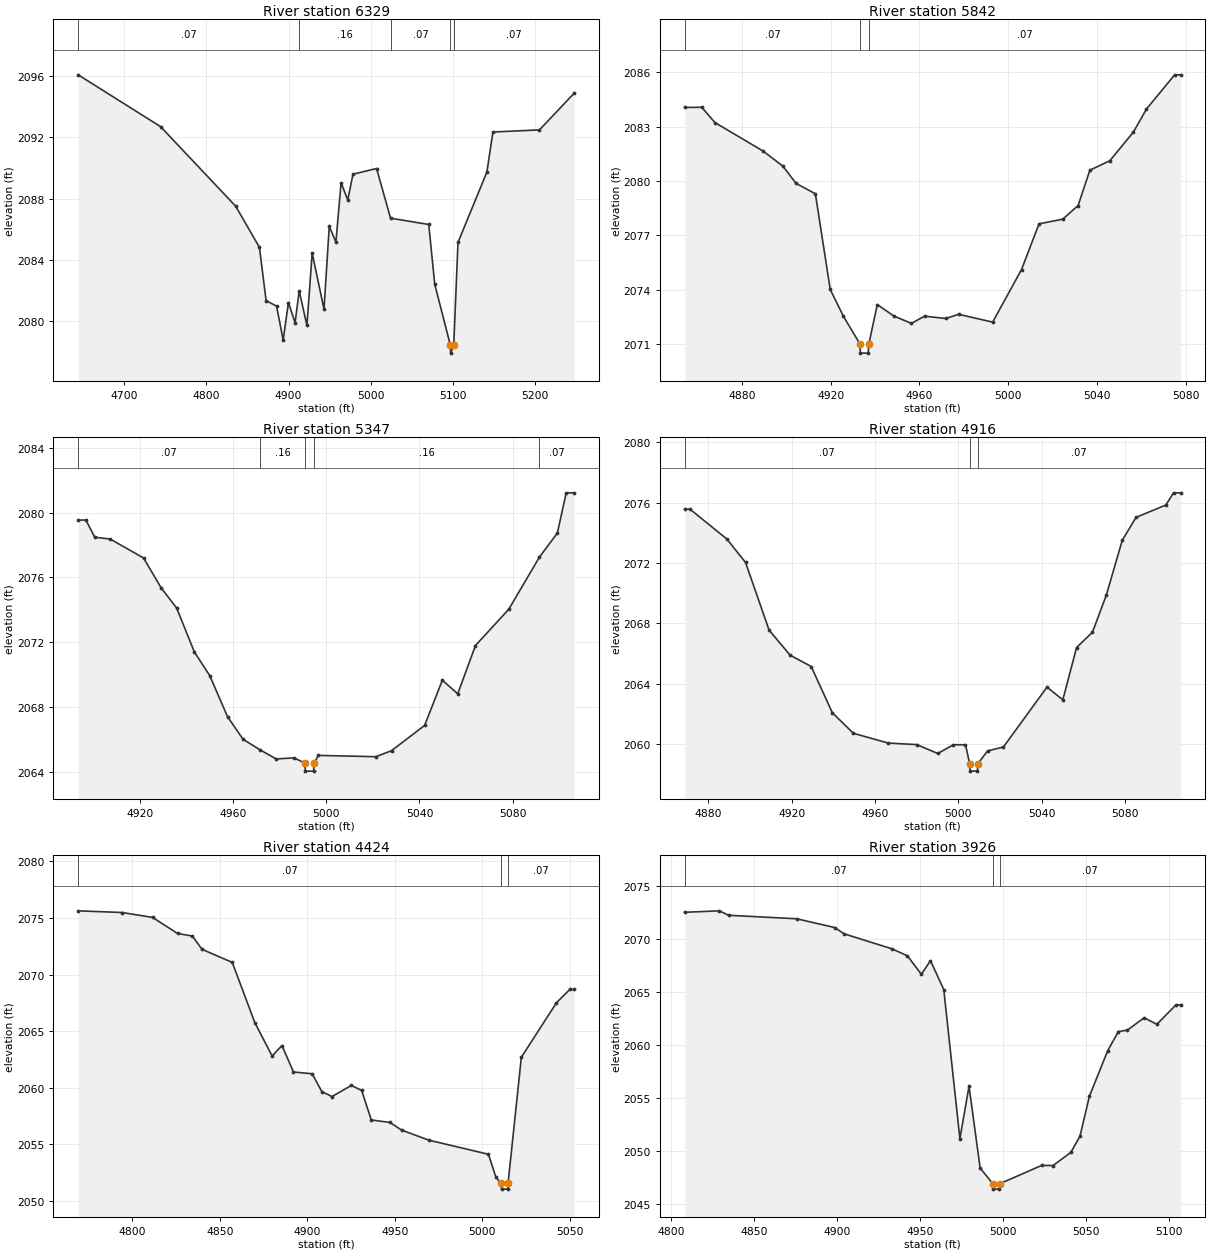
Type RM Length L Ch R = 1,6329,487,487,487
BEGIN DESCRIPTION:
Rock Creek Trib1 12.0
END DESCRIPTION:
XS GIS Cut Line= 3
      1390105.02      6878388.02      1389885.20      6878107.86
      1389705.03      6877938.03
#Sta/Elev= 30
  4643.9 2096.08  4744.2 2092.70  4835.6 2087.51  4864.5 2084.83  4872.6 2081.36
  4885.4 2080.99  4893.4 2078.78  4899.8 2081.23  4907.9 2079.91  4912.9 2081.99
  4922.3 2079.74  4928.7 2084.45  4943.1 2080.80  4949.5 2086.20  4957.6 2085.17
  4963.9 2089.04  4972.0 2087.92  4978.4 2089.60  5007.1 2089.97  5024.1 2086.73
  5070.6 2086.32  5077.9 2082.42  5097.0 2078.43  5097.2 2077.93  5101.0 2078.43
  5106.2 2085.15  5141.4 2089.74  5148.7 2092.35  5205.4 2092.49  5247.6 2094.88
#Mann=5,-1,0
  4643.9    0.07       0  4912.9    0.16       0  5024.1    0.07       0
  5097.0    0.07       0  5101.0    0.07       0
Bank Sta=5097,5101
Exp/Cntr=0.3,0.1

Type RM Length L Ch R = 1,5842,495,495,495
BEGIN DESCRIPTION:
Rock Creek Trib1 11.0
END DESCRIPTION:
XS GIS Cut Line= 3
      1390305.02      6877988.04      1390228.12      6877864.17
      1390154.97      6877837.99
#Sta/Elev= 30
  4854.2 2084.06  4861.9 2084.07  4867.8 2083.23  4889.6 2081.65  4898.5 2080.82
  4904.4 2079.87  4913.1 2079.30  4919.8 2074.02  4925.7 2072.55  4933.2 2071.01
  4933.4 2070.51  4936.9 2070.51  4937.2 2071.01  4941.0 2073.19  4948.4 2072.56
  4956.4 2072.15  4962.3 2072.55  4971.8 2072.42  4977.7 2072.65  4993.0 2072.22
  5006.0 2075.12  5013.9 2077.64  5024.6 2077.90  5031.5 2078.65  5036.8 2080.60
  5045.8 2081.12  5056.4 2082.70  5062.3 2083.97  5075.0 2085.86  5077.7 2085.86
#Mann=3,-1,0
  4854.2    0.07       0  4933.2    0.07       0  4937.2    0.07       0
Bank Sta=4933.2,4937.2
Exp/Cntr=0.3,0.1

Type RM Length L Ch R = 1,5347,431,431,431
BEGIN DESCRIPTION:
Rock Creek Trib1 10.0
END DESCRIPTION:
XS GIS Cut Line= 3
      1390704.97      6877687.97      1390624.98      6877617.96
      1390554.97      6877537.97
#Sta/Elev= 30
  4893.7 2079.54  4897.0 2079.54  4900.8 2078.48  4907.4 2078.37  4921.7 2077.20
  4929.3 2075.35  4935.9 2074.11  4943.5 2071.40  4950.1 2069.94  4957.7 2067.41
  4964.4 2066.01  4971.7 2065.36  4978.6 2064.80  4986.2 2064.87  4990.8 2064.55
  4991.1 2064.05  4994.6 2064.05  4994.8 2064.55  4996.7 2065.02  5021.3 2064.94
  5028.0 2065.31  5042.2 2066.87  5049.8 2069.66  5056.4 2068.82  5064.0 2071.80
  5078.3 2074.04  5091.4 2077.25  5099.1 2078.74  5102.9 2081.22  5106.3 2081.22
#Mann=5,-1,0
  4893.7    0.07       0  4971.7    0.16       0  4990.8    0.07       0
  4994.8    0.16       0  5091.4    0.07       0
Bank Sta=4990.8,4994.8
Exp/Cntr=0.3,0.1

Type RM Length L Ch R = 1,4916,492,492,492
BEGIN DESCRIPTION:
Rock Creek Trib1 9.0
END DESCRIPTION:
XS GIS Cut Line= 3
      1391005.00      6877538.02      1390985.16      6877408.22
      1390904.98      6877337.98
#Sta/Elev= 30
  4868.7 2075.57  4871.2 2075.57  4888.9 2073.59  4897.9 2072.03  4909.2 2067.54
  4919.3 2065.88  4929.4 2065.13  4939.5 2062.07  4949.6 2060.70  4966.4 2060.05
  4980.0 2059.95  4990.1 2059.36  4997.6 2059.94  5003.4 2059.94  5005.4 2058.69
  5005.6 2058.19  5009.1 2058.19  5009.4 2058.69  5014.0 2059.53  5021.6 2059.79
  5042.5 2063.76  5050.1 2062.92  5056.7 2066.39  5064.3 2067.40  5071.0 2069.88
  5078.6 2073.50  5085.2 2075.02  5099.5 2075.84  5103.2 2076.65  5106.6 2076.65
#Mann=3,-1,0
  4868.7    0.07       0  5005.4    0.07       0  5009.4    0.07       0
Bank Sta=5005.4,5009.4
Exp/Cntr=0.3,0.1

Type RM Length L Ch R = 1,4424,498,498,498
BEGIN DESCRIPTION:
Rock Creek Trib1 8.0
END DESCRIPTION:
XS GIS Cut Line= 3
      1391301.04      6877599.43      1391399.06      6877390.25
      1391405.00      6877337.99
#Sta/Elev= 30
  4769.0 2075.64  4794.1 2075.49  4811.5 2075.06  4825.8 2073.64  4834.3 2073.41
  4839.8 2072.24  4857.1 2071.08  4870.0 2065.76  4879.9 2062.81  4885.5 2063.74
  4892.1 2061.40  4902.8 2061.24  4908.3 2059.67  4914.1 2059.23  4925.2 2060.21
  4931.1 2059.77  4936.6 2057.16  4947.3 2056.94  4953.9 2056.27  4969.4 2055.38
  5003.6 2054.13  5007.8 2052.12  5010.8 2051.55  5011.1 2051.05  5014.6 2051.05
  5014.8 2051.55  5022.4 2062.70  5042.5 2067.52  5050.1 2068.69  5052.6 2068.69
#Mann=3,-1,0
  4769.0    0.07       0  5010.8    0.07       0  5014.8    0.07       0
Bank Sta=5010.8,5014.8
Exp/Cntr=0.3,0.1

Type RM Length L Ch R = 1,3926,498,498,498
BEGIN DESCRIPTION:
Rock Creek Trib1 7.0
END DESCRIPTION:
XS GIS Cut Line= 3
      1391770.72      6877610.48      1391848.89      6877435.33
      1391804.99      6877337.97
#Sta/Elev= 30
  4808.2 2072.52  4829.1 2072.66  4834.6 2072.24  4875.6 2071.91  4898.5 2071.08
  4904.3 2070.48  4933.0 2069.07  4942.3 2068.41  4950.7 2066.66  4956.2 2067.95
  4964.2 2065.22  4973.9 2051.12  4979.4 2056.08  4986.1 2048.35  4993.8 2046.86
  4994.0 2046.36  4997.5 2046.36  4997.8 2046.86  5023.1 2048.60  5030.0 2048.59
  5040.7 2049.83  5046.2 2051.36  5051.9 2055.14  5062.9 2059.44  5069.3 2061.24
  5074.8 2061.39  5084.8 2062.55  5092.5 2061.94  5104.0 2063.77  5106.8 2063.77
#Mann=3,-1,0
  4808.2    0.07       0  4993.8    0.07       0  4997.8    0.07       0
Bank Sta=4993.8,4997.8
Exp/Cntr=0.3,0.1

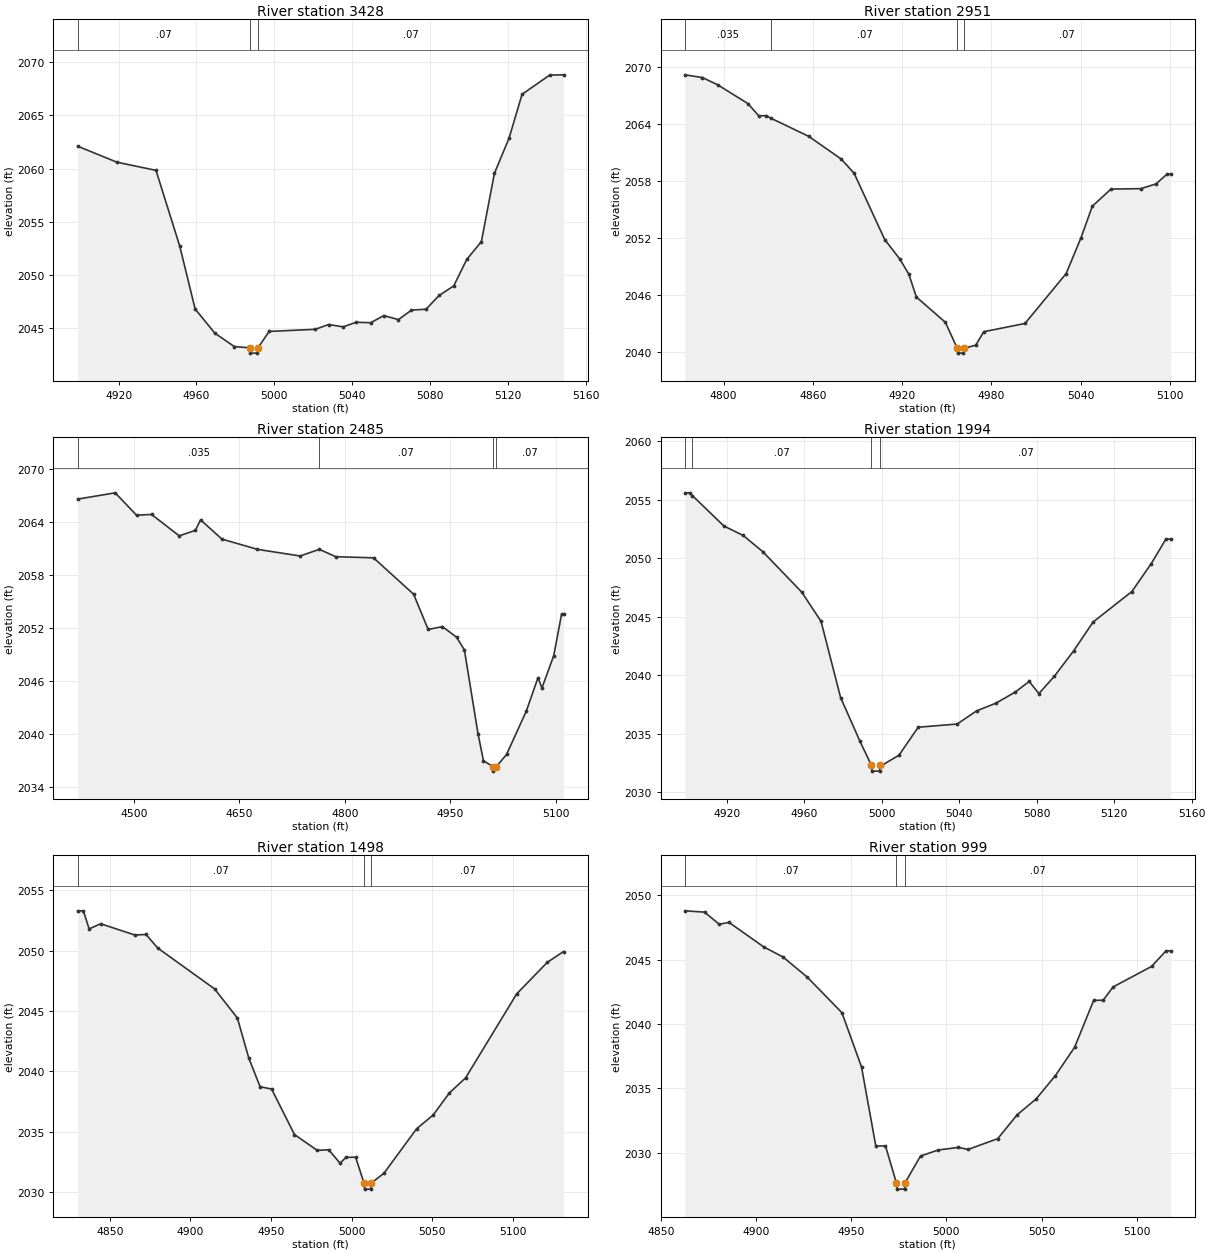
Type RM Length L Ch R = 1,3428,477,477,477
BEGIN DESCRIPTION:
Rock Creek Trib1 6.0
END DESCRIPTION:
XS GIS Cut Line= 3
      1392305.00      6877438.03      1392315.19      6877337.54
      1392205.00      6877238.00
#Sta/Elev= 30
  4899.0 2062.10  4919.1 2060.60  4939.2 2059.83  4951.4 2052.71  4959.3 2046.80
  4969.4 2044.53  4979.4 2043.27  4987.4 2043.15  4987.6 2042.65  4991.3 2042.65
  4991.6 2043.15  4997.3 2044.69  5021.1 2044.89  5027.8 2045.34  5035.3 2045.12
  5042.0 2045.55  5049.5 2045.51  5056.2 2046.18  5063.7 2045.80  5070.4 2046.69
  5077.9 2046.78  5084.6 2048.07  5092.1 2048.97  5098.8 2051.46  5106.3 2053.13
  5113.0 2059.55  5120.5 2062.85  5127.2 2066.98  5141.4 2068.79  5148.5 2068.81
#Mann=3,-1,0
  4899.0    0.07       0  4987.4    0.07       0  4991.6    0.07       0
Bank Sta=4987.4,4991.6
Exp/Cntr=0.3,0.1

Type RM Length L Ch R = 1,2951,466,466,466
BEGIN DESCRIPTION:
Rock Creek Trib1 5.0
END DESCRIPTION:
XS GIS Cut Line= 3
      1392699.65      6877709.53      1392744.95      6877488.12
      1392755.00      6877388.02
#Sta/Elev= 30
  4774.0 2069.20  4785.8 2068.91  4796.0 2068.15  4816.4 2066.16  4823.6 2064.88
  4828.7 2064.89  4832.1 2064.60  4857.2 2062.71  4879.1 2060.31  4887.8 2058.80
  4908.3 2051.82  4918.5 2049.75  4924.5 2048.17  4929.6 2045.75  4949.1 2043.08
  4957.1 2040.33  4957.4 2039.83  4961.1 2039.83  4961.4 2040.33  4969.5 2040.67
  4974.9 2042.09  5002.6 2042.96  5030.3 2048.23  5040.3 2052.02  5047.9 2055.34
  5060.4 2057.14  5080.5 2057.19  5090.6 2057.68  5098.1 2058.72  5100.6 2058.72
#Mann=4,-1,0
  4774.0   0.035       0  4832.1    0.07       0  4957.1    0.07       0
  4961.4    0.07       0
Bank Sta=4957.1,4961.4
Exp/Cntr=0.3,0.1

Type RM Length L Ch R = 1,2485,491,491,491
BEGIN DESCRIPTION:
Rock Creek Trib1 4.0
END DESCRIPTION:
XS GIS Cut Line= 3
      1393145.96      6877810.70      1393054.67      6877237.62
      1392955.03      6877188.02
#Sta/Elev= 30
  4419.7 2066.56  4473.1 2067.27  4503.4 2064.74  4524.9 2064.82  4564.2 2062.40
  4587.1 2063.02  4594.6 2064.21  4625.0 2062.03  4675.6 2060.87  4736.3 2060.12
  4763.7 2060.87  4787.0 2060.04  4840.8 2059.91  4897.9 2055.79  4918.6 2051.80
  4938.9 2052.12  4959.1 2050.92  4970.2 2049.47  4989.5 2040.02  4997.3 2036.93
  5011.2 2036.26  5011.5 2035.76  5015.5 2036.26  5030.2 2037.65  5058.2 2042.54
  5075.0 2046.35  5080.5 2045.16  5097.4 2048.85  5108.5 2053.54  5111.3 2053.54
#Mann=4,-1,0
  4419.7   0.035       0  4763.7    0.07       0  5011.2    0.07       0
  5015.5    0.07       0
Bank Sta=5011.2,5015.5
Exp/Cntr=0.3,0.1

Type RM Length L Ch R = 1,1994,496,496,496
BEGIN DESCRIPTION:
Rock Creek Trib1 3.0
END DESCRIPTION:
XS GIS Cut Line= 3
      1393505.00      6877387.96      1393494.50      6877286.80
      1393505.00      6877137.97
#Sta/Elev= 30
  4898.3 2055.57  4900.8 2055.57  4902.2 2055.33  4918.4 2052.74  4928.4 2051.93
  4938.5 2050.55  4958.6 2047.10  4968.6 2044.60  4978.7 2038.09  4988.7 2034.36
  4994.6 2032.31  4994.9 2031.81  4998.8 2031.81  4999.1 2032.31  5000.0 2032.31
  5008.8 2033.16  5018.8 2035.56  5038.9 2035.83  5048.9 2036.95  5058.9 2037.61
  5069.0 2038.57  5076.1 2039.47  5081.1 2038.43  5089.0 2039.89  5099.0 2042.07
  5109.1 2044.54  5129.1 2047.14  5139.1 2049.52  5146.7 2051.62  5149.2 2051.62
#Mann=4,-1,0
  4898.3   0.035       0  4902.2    0.07       0  4994.6    0.07       0
  4999.1    0.07       0
Bank Sta=4994.6,4999.1
Exp/Cntr=0.3,0.1

Type RM Length L Ch R = 1,1498,499,499,499
BEGIN DESCRIPTION:
Rock Creek Trib1 2.0
END DESCRIPTION:
XS GIS Cut Line= 3
      1393804.99      6877388.01      1393925.02      6877267.77
      1393905.00      6877138.00
#Sta/Elev= 30
  4830.1 2053.29  4833.6 2053.29  4837.2 2051.79  4844.3 2052.22  4865.5 2051.29
  4872.5 2051.33  4879.6 2050.22  4915.0 2046.82  4929.1 2044.41  4936.2 2041.08
  4943.2 2038.72  4950.3 2038.53  4964.5 2034.76  4978.6 2033.45  4985.7 2033.50
  4992.8 2032.38  4996.4 2032.88  5002.4 2032.88  5007.6 2030.74  5007.9 2030.24
  5011.8 2030.24  5012.1 2030.74  5020.0 2031.56  5040.2 2035.24  5050.4 2036.37
  5060.5 2038.20  5070.6 2039.46  5102.3 2046.42  5121.2 2049.02  5131.3 2049.92
#Mann=3,-1,0
  4830.1    0.07       0  5007.6    0.07       0  5012.1    0.07       0
Bank Sta=5007.6,5012.1
Exp/Cntr=0.3,0.1

Type RM Length L Ch R = 1,999,500,500,500
BEGIN DESCRIPTION:
Rock Creek Trib1 1.0
END DESCRIPTION:
XS GIS Cut Line= 3
      1394304.99      6877538.02      1394338.48      6877404.77
      1394355.00      6877288.03
#Sta/Elev= 30
  4862.6 2048.78  4872.9 2048.68  4880.6 2047.74  4885.8 2047.88  4903.9 2045.99
  4914.2 2045.19  4926.9 2043.63  4945.1 2040.87  4955.4 2036.66  4962.9 2030.53
  4968.0 2030.52  4973.7 2027.67  4974.1 2027.17  4978.0 2027.17  4978.3 2027.67
  4986.4 2029.74  4995.8 2030.21  5006.3 2030.41  5011.4 2030.25  5027.0 2031.09
  5037.1 2032.93  5047.2 2034.18  5057.3 2035.99  5067.4 2038.19  5077.4 2041.83
  5082.4 2041.84  5087.6 2042.87  5107.8 2044.46  5115.4 2045.67  5117.9 2045.67
#Mann=3,-1,0
  4862.6    0.07       0  4973.7    0.07       0  4978.3    0.07       0
Bank Sta=4973.7,4978.3
Exp/Cntr=0.3,0.1

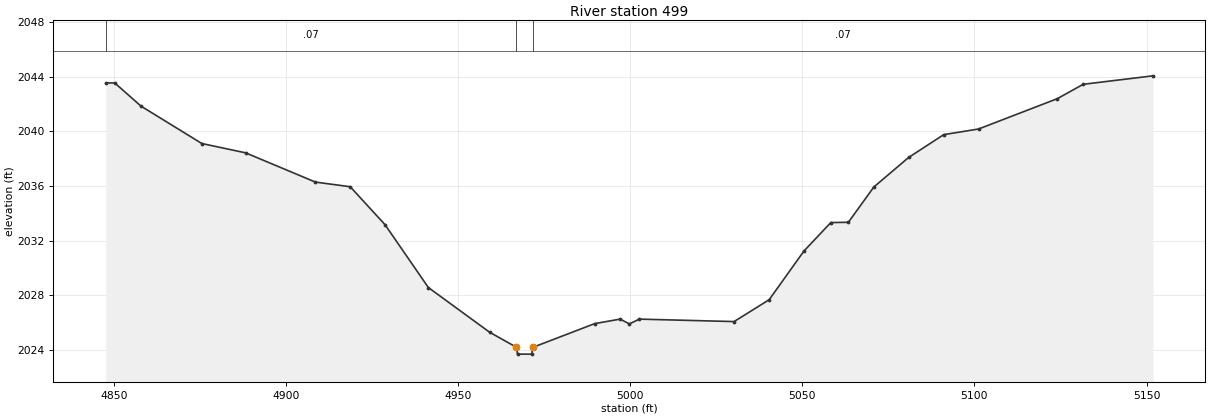
Type RM Length L Ch R = 1,499,0,0,0
BEGIN DESCRIPTION:
Bitter Creek Trib8T3 35.0
END DESCRIPTION:
XS GIS Cut Line= 3
      1394755.00      6877688.02      1394780.08      6877537.80
      1394755.00      6877387.99
#Sta/Elev= 30
  4847.7 2043.53  4850.3 2043.53  4857.9 2041.84  4875.6 2039.10  4888.3 2038.42
  4908.6 2036.28  4918.7 2035.94  4928.8 2033.17  4941.4 2028.57  4959.2 2025.30
  4967.0 2024.20  4967.3 2023.70  4971.4 2023.70  4971.8 2024.20  4989.7 2025.93
  4997.1 2026.26  4999.8 2025.91  5002.7 2026.26  5030.2 2026.08  5040.4 2027.68
  5050.5 2031.24  5058.3 2033.32  5063.4 2033.34  5070.8 2035.92  5080.9 2038.08
  5091.1 2039.75  5101.2 2040.16  5124.1 2042.38  5131.6 2043.43  5151.9 2044.05
#Mann=3,-1,0
  4847.7    0.07       0  4967.0    0.07       0  4971.8    0.07       0
Bank Sta=4967,4971.8
Exp/Cntr=0.3,0.1

Chan Stop Cuts=-1