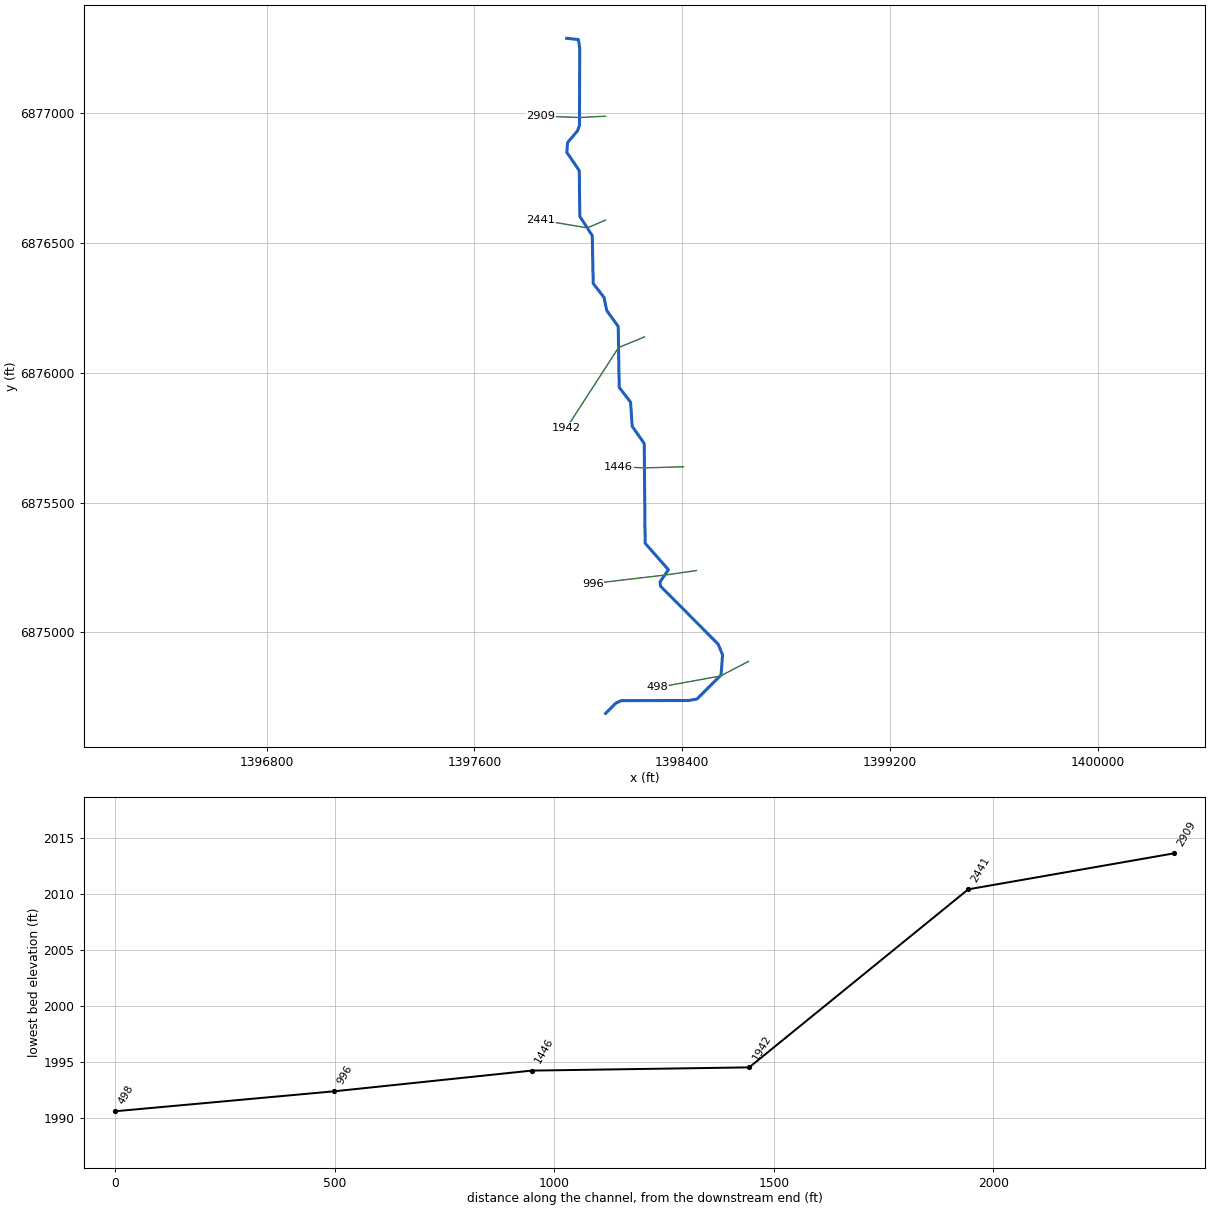
--- Rock Creek Trib2.prj (project) ---

Proj Title=Rock Creek Trib2 Base Level Engineering
Current Plan=p01
Default Exp/Contr=0.3,0.1
English Units
Geom File=g01
Flow File=f01
Plan File=p01
BEGIN DESCRIPTION:
Rock Creek Trib2
END DESCRIPTION:

--- Rock Creek Trib2.p01 (plan) ---

Plan Title=Multiple Run
Short Identifier=Multiple
Geom File=g01
Flow File=f01
Subcritical Flow
K Sum by GR= 0
Std Step Tol= 0.01
Critical Tol= 0.01
Num of Std Step Trials= 20
Max Error Tol= 0.3
Flow Tol Ratio= 0.001
Split Flow NTrial= 30
Split Flow Tol= 0.02
Split Flow Ratio= 0.02
Log Output Level= 0
Friction Slope Method= 1
Unsteady Friction Slope Method= 2
Unsteady Bridges Friction Slope Method= 1
Parabolic Critical Depth
Global Vel Dist=  1 , 1 , 1
Global Log Level= 0
CheckData=True
Encroach Param= -1, 0, 0, 0
BEGIN DESCRIPTION:
Multiple Run
END DESCRIPTION:

--- Rock Creek Trib2.f01 (steady flow) ---

Flow Title=Multiple
Number of Profiles=7
Profile Names=10-year,25-year,50-year,1pct_min,100-year,1pct_plu,500-year
River Rch & RM= Rock Creek Trib2,Reach-1,2909
     120     162     194     117     233     465     338
Boundary for River Rch & Prof#=Rock Creek Trib2,Reach-1,1
Up Type=0
Dn Type=3
Dn Slope=0.005
Boundary for River Rch & Prof#=Rock Creek Trib2,Reach-1,2
Up Type=0
Dn Type=3
Dn Slope=0.005
Boundary for River Rch & Prof#=Rock Creek Trib2,Reach-1,3
Up Type=0
Dn Type=3
Dn Slope=0.005
Boundary for River Rch & Prof#=Rock Creek Trib2,Reach-1,4
Up Type=0
Dn Type=3
Dn Slope=0.005
Boundary for River Rch & Prof#=Rock Creek Trib2,Reach-1,5
Up Type=0
Dn Type=3
Dn Slope=0.005
Boundary for River Rch & Prof#=Rock Creek Trib2,Reach-1,6
Up Type=0
Dn Type=3
Dn Slope=0.005
Boundary for River Rch & Prof#=Rock Creek Trib2,Reach-1,7
Up Type=0
Dn Type=3
Dn Slope=0.005

--- Rock Creek Trib2.g01 (geometry) ---

Geom Title=Existing Conditions

River Reach=Rock Creek Trib2,Reach-1
Reach XY= 30
      1397955.00      6877288.00      1398000.37      6877283.37
      1398005.45      6877248.45      1398004.30      6876951.91
      1397996.81      6876931.92      1397958.37      6876886.26
      1397955.77      6876848.69      1398003.60      6876778.35
      1398005.69      6876601.92      1398053.62      6876528.34
      1398057.24      6876343.93      1398098.88      6876290.18
      1398109.19      6876239.74      1398153.64      6876178.35
      1398157.26      6875943.94      1398201.14      6875886.40
      1398207.47      6875793.57      1398253.78      6875727.50
      1398257.19      6875343.44      1398346.98      6875241.33
      1398314.62      6875194.67      1398316.24      6875178.00
      1398538.60      6874954.75      1398555.51      6874913.03
      1398549.61      6874835.56      1398457.47      6874743.45
      1398425.18      6874737.57      1398165.40      6874737.04
      1398145.02      6874727.95      1398105.00      6874688.00

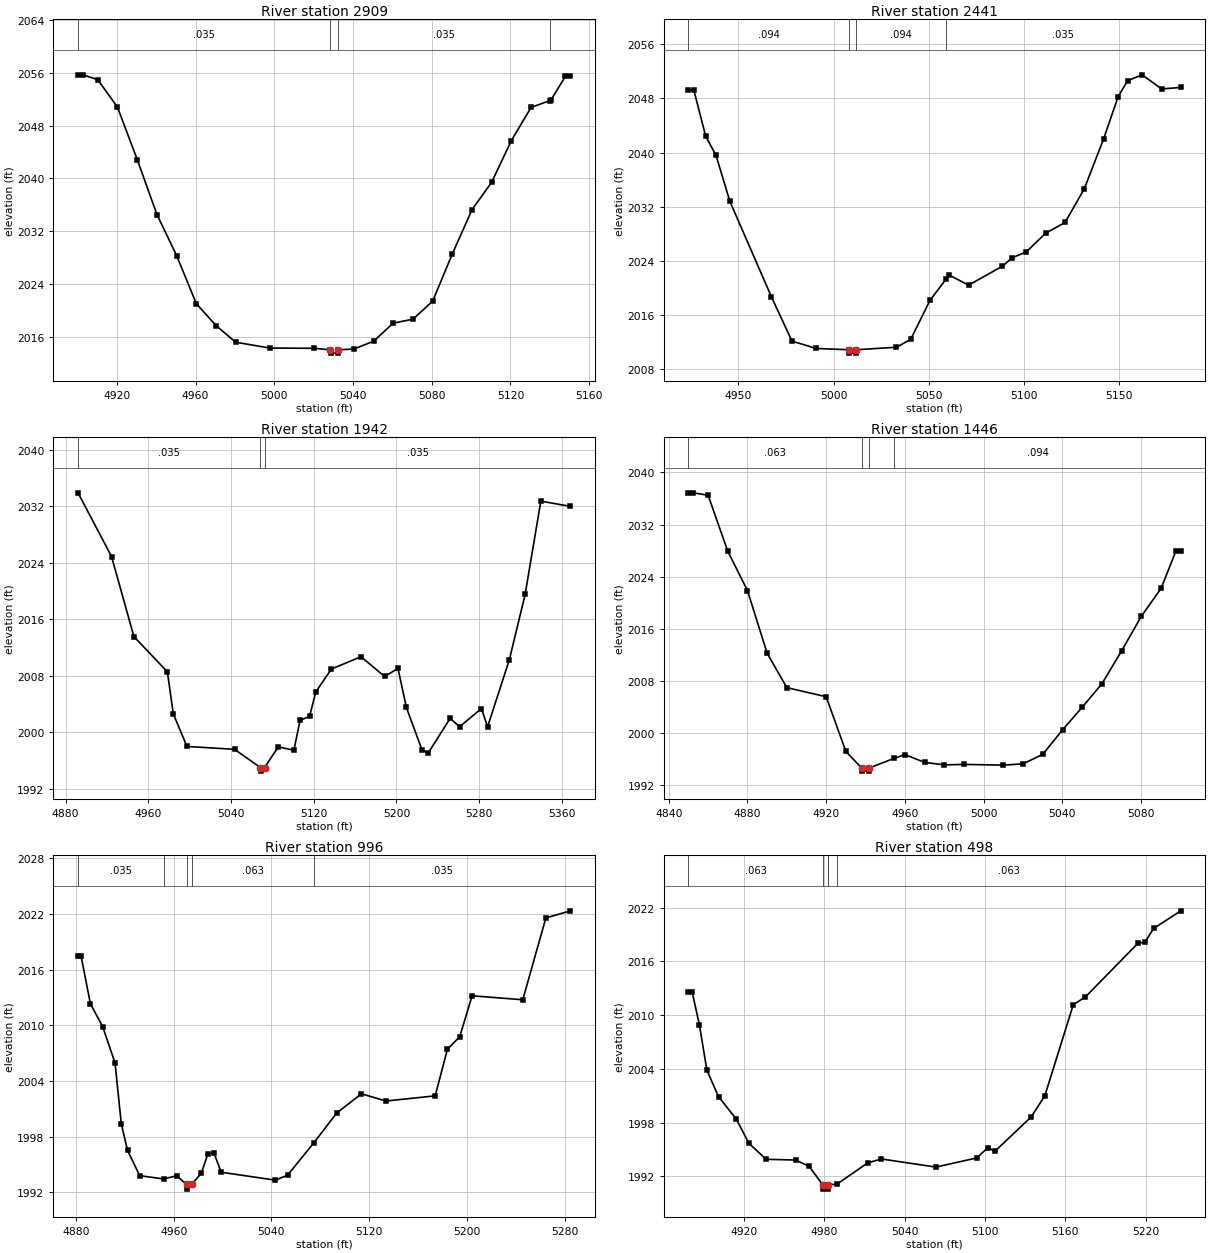
Type RM Length L Ch R = 1,2909,468,468,468
BEGIN DESCRIPTION:
Rock Creek Trib2 5.0
END DESCRIPTION:
XS GIS Cut Line= 3
      1398105.02      6876988.00      1398005.43      6876983.27
      1397855.01      6876988.00
#Sta/Elev= 30
  4900.3 2055.67  4902.8 2055.67  4910.3 2054.94  4920.3 2050.81  4930.4 2042.85
  4940.4 2034.55  4950.4 2028.34  4960.4 2021.08  4970.4 2017.77  4980.4 2015.25
  4997.7 2014.37  5020.4 2014.33  5028.4 2014.10  5028.7 2013.60  5032.2 2013.60
  5032.4 2014.10  5040.5 2014.22  5050.5 2015.40  5060.5 2018.14  5070.5 2018.73
  5080.5 2021.46  5090.5 2028.61  5100.5 2035.29  5110.5 2039.44  5120.5 2045.74
  5130.5 2050.74  5139.9 2051.75  5140.5 2051.81  5148.0 2055.46  5150.5 2055.46
#Mann=4,-1,0
  4900.3   0.035       0  5028.4   0.035       0  5032.4   0.035       0
  5139.9    0.07       0
Bank Sta=5028.4,5032.4
Exp/Cntr=0.3,0.1

Type RM Length L Ch R = 1,2441,499,499,499
BEGIN DESCRIPTION:
Rock Creek Trib2 4.0
END DESCRIPTION:
XS GIS Cut Line= 3
      1398105.03      6876588.01      1398034.90      6876557.96
      1397854.99      6876588.00
#Sta/Elev= 30
  4923.7 2049.26  4926.5 2049.26  4932.8 2042.40  4938.2 2039.58  4945.5 2032.78
  4967.3 2018.71  4978.1 2012.17  4990.8 2011.08  5008.0 2010.89  5008.3 2010.39
  5011.8 2010.39  5012.0 2010.89  5033.0 2011.26  5040.5 2012.43  5050.6 2018.17
  5059.0 2021.29  5060.7 2021.92  5070.9 2020.42  5088.7 2023.23  5093.8 2024.46
  5101.3 2025.36  5111.4 2028.10  5121.6 2029.68  5131.7 2034.66  5141.8 2041.98
  5149.5 2048.28  5154.5 2050.62  5162.1 2051.48  5172.3 2049.40  5182.4 2049.61
#Mann=4,-1,0
  4923.7   0.094       0  5008.0    0.07       0  5012.0   0.094       0
  5059.0   0.035       0
Bank Sta=5008,5012
Exp/Cntr=0.3,0.1

Type RM Length L Ch R = 1,1942,496,496,496
BEGIN DESCRIPTION:
Rock Creek Trib2 3.0
END DESCRIPTION:
XS GIS Cut Line= 3
      1398254.97      6876137.99      1398155.11      6876097.13
      1397955.03      6875788.04
#Sta/Elev= 30
  4892.1 2033.93  4924.5 2024.90  4946.1 2013.56  4978.5 2008.55  4984.2 2002.61
  4997.4 1997.98  5043.4 1997.57  5068.5 1994.98  5068.8 1994.48  5072.5 1994.98
  5085.7 1997.92  5100.8 1997.44  5106.8 2001.67  5116.0 2002.24  5121.9 2005.69
  5137.1 2008.95  5165.7 2010.70  5188.5 2007.90  5201.5 2009.03  5209.6 2003.50
  5224.8 1997.45  5230.7 1997.04  5251.9 2001.96  5261.0 2000.77  5282.2 2003.35
  5288.1 2000.76  5309.2 2010.29  5324.4 2019.52  5339.6 2032.75  5368.2 2032.01
#Mann=3,-1,0
  4892.1   0.035       0  5068.5   0.035       0  5072.5   0.035       0
Bank Sta=5068.5,5072.5
Exp/Cntr=0.3,0.1

Type RM Length L Ch R = 1,1446,450,450,450
BEGIN DESCRIPTION:
Rock Creek Trib2 2.0
END DESCRIPTION:
XS GIS Cut Line= 3
      1398404.99      6875638.00      1398255.06      6875633.48
      1398154.96      6875638.00
#Sta/Elev= 29
  4850.0 2036.88  4852.5 2036.88  4860.0 2036.51  4870.0 2027.92  4880.0 2021.89
  4890.0 2012.28  4900.0 2007.00  4920.0 2005.60  4930.0 1997.21  4938.0 1994.69
  4938.3 1994.19  4941.8 1994.19  4942.0 1994.69  4954.6 1996.15  4960.0 1996.73
  4970.0 1995.53  4980.1 1995.15  4990.1 1995.22  5010.1 1995.11  5020.1 1995.31
  5030.1 1996.78  5040.1 2000.52  5050.1 2003.99  5060.1 2007.58  5070.1 2012.62
  5080.1 2017.92  5090.2 2022.23  5097.7 2027.94  5100.2 2027.94
#Mann=4,-1,0
  4850.0   0.063       0  4938.0    0.07       0  4942.0   0.063       0
  4954.6   0.094       0
Bank Sta=4938,4942
Exp/Cntr=0.3,0.1

Type RM Length L Ch R = 1,996,498,498,498
BEGIN DESCRIPTION:
Rock Creek Trib2 1.0
END DESCRIPTION:
XS GIS Cut Line= 3
      1398455.00      6875238.00      1398337.88      6875221.33
      1398055.03      6875188.00
#Sta/Elev= 30
  4881.7 2017.47  4884.2 2017.47  4891.8 2012.34  4901.9 2009.85  4912.0 2005.94
  4917.1 1999.40  4922.2 1996.52  4932.2 1993.79  4951.8 1993.44  4962.5 1993.78
  4970.6 1992.84  4970.9 1992.34  4974.6 1992.84  4982.7 1994.06  4988.0 1996.16
  4993.0 1996.23  4998.9 1994.16  5043.2 1993.31  5053.2 1993.84  5074.5 1997.29
  5093.5 2000.55  5113.7 2002.62  5133.8 2001.84  5174.1 2002.40  5184.1 2007.42
  5194.2 2008.78  5204.3 2013.19  5245.8 2012.76  5264.7 2021.58  5284.8 2022.35
#Mann=5,-1,0
  4881.7   0.035       0  4951.8   0.063       0  4970.6   0.063       0
  4974.6   0.063       0  5074.5   0.035       0
Bank Sta=4970.6,4974.6
Exp/Cntr=0.3,0.1

Type RM Length L Ch R = 1,498,0,0,0
BEGIN DESCRIPTION:
Rock Creek Trib2 2136
END DESCRIPTION:
XS GIS Cut Line= 3
      1398654.98      6874887.99      1398547.25      6874831.81
      1398304.98      6874788.00
#Sta/Elev= 30
  4878.5 2012.55  4881.3 2012.55  4886.7 2008.92  4892.3 2003.83  4901.0 2000.89
  4914.4 1998.35  4923.6 1995.69  4936.5 1993.89  4958.6 1993.81  4968.7 1993.10
  4978.7 1991.06  4979.0 1990.56  4982.5 1990.56  4982.7 1991.06  4983.1 1991.06
  4989.4 1991.11  5012.4 1993.49  5022.6 1993.93  5063.3 1993.02  5093.7 1994.04
  5102.3 1995.20  5107.3 1994.78  5134.4 1998.61  5144.6 2000.96  5165.9 2011.15
  5175.0 2012.03  5214.3 2018.03  5219.4 2018.13  5225.9 2019.67  5246.2 2021.64
#Mann=5,-1,0
  4878.5   0.063       0  4978.7   0.063       0  4982.7   0.063       0
  4983.1   0.035       0  4989.4   0.063       0
Bank Sta=4978.7,4982.7
Exp/Cntr=0.3,0.1

Chan Stop Cuts=-1