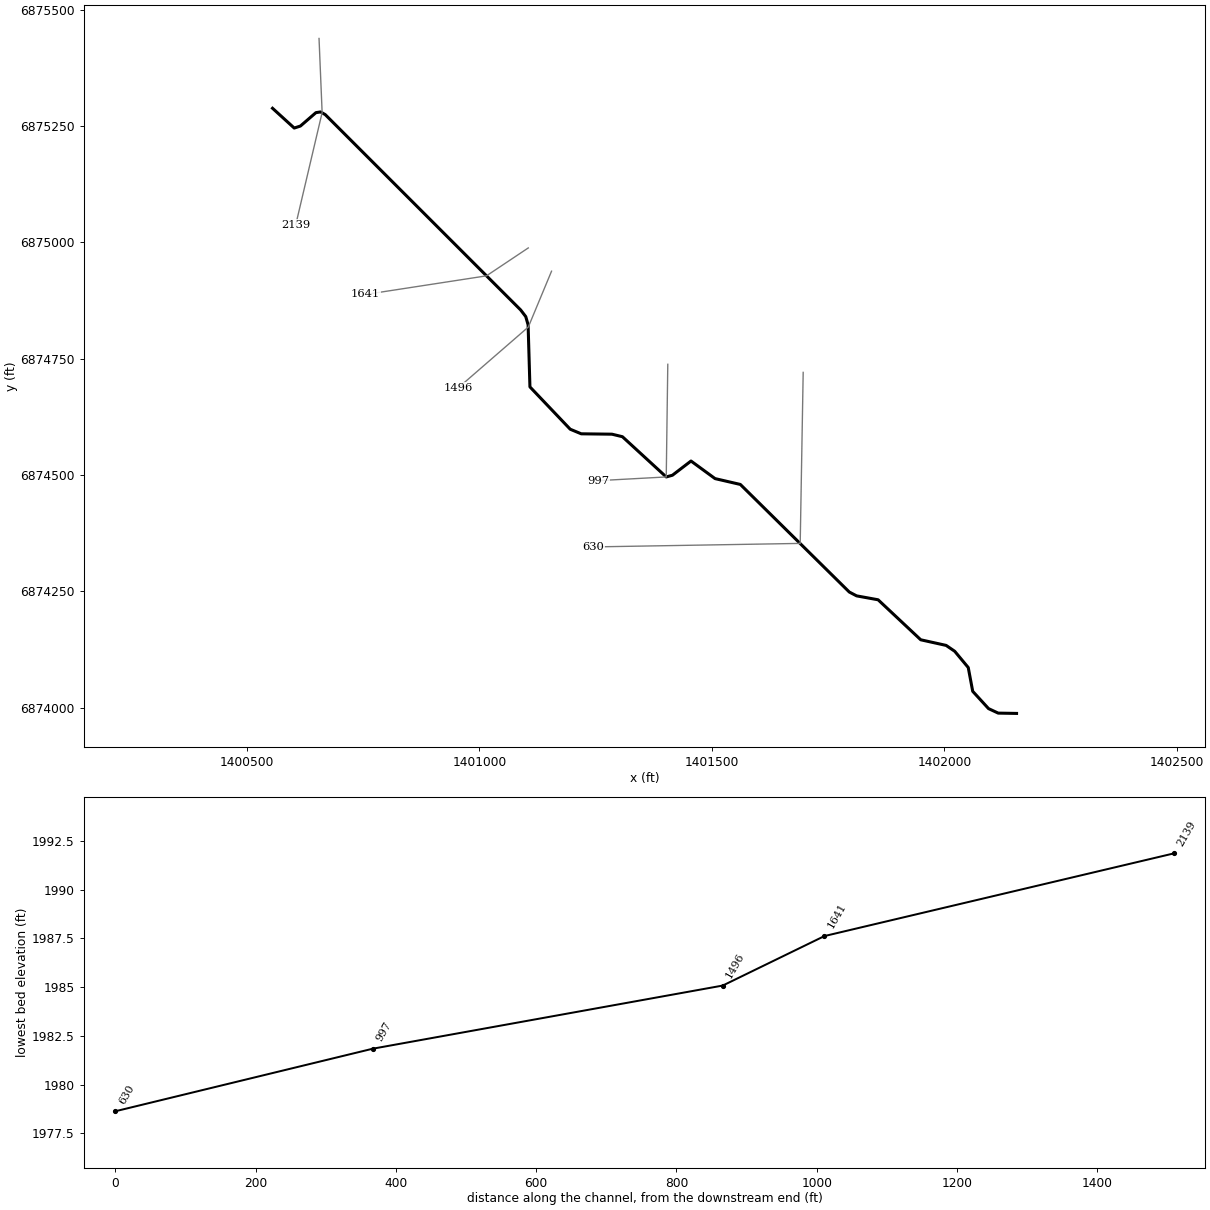
--- Rock Creek Trib3.prj (project) ---

Proj Title=Rock Creek Trib3 Base Level Engineering
Current Plan=p01
Default Exp/Contr=0.3,0.1
English Units
Geom File=g01
Flow File=f01
Plan File=p01
BEGIN DESCRIPTION:
Rock Creek Trib3
END DESCRIPTION:

--- Rock Creek Trib3.p01 (plan) ---

Plan Title=Multiple Run
Short Identifier=Multiple
Geom File=g01
Flow File=f01
Subcritical Flow
K Sum by GR= 0
Std Step Tol= 0.01
Critical Tol= 0.01
Num of Std Step Trials= 20
Max Error Tol= 0.3
Flow Tol Ratio= 0.001
Split Flow NTrial= 30
Split Flow Tol= 0.02
Split Flow Ratio= 0.02
Log Output Level= 0
Friction Slope Method= 1
Unsteady Friction Slope Method= 2
Unsteady Bridges Friction Slope Method= 1
Parabolic Critical Depth
Global Vel Dist=  1 , 1 , 1
Global Log Level= 0
CheckData=True
Encroach Param= -1, 0, 0, 0
BEGIN DESCRIPTION:
Multiple Run
END DESCRIPTION:

--- Rock Creek Trib3.f01 (steady flow) ---

Flow Title=Multiple
Number of Profiles=7
Profile Names=10-year,25-year,50-year,1pct_min,100-year,1pct_plu,500-year
River Rch & RM= Rock Creek Trib3,Reach-1,2139
     269     379     471     291     581    1159     896
River Rch & RM= Rock Creek Trib3,Reach-1,1641
     275     388     483     299     597    1191     922
Boundary for River Rch & Prof#=Rock Creek Trib3,Reach-1,1
Up Type=0
Dn Type=3
Dn Slope=0.005
Boundary for River Rch & Prof#=Rock Creek Trib3,Reach-1,2
Up Type=0
Dn Type=3
Dn Slope=0.005
Boundary for River Rch & Prof#=Rock Creek Trib3,Reach-1,3
Up Type=0
Dn Type=3
Dn Slope=0.005
Boundary for River Rch & Prof#=Rock Creek Trib3,Reach-1,4
Up Type=0
Dn Type=3
Dn Slope=0.005
Boundary for River Rch & Prof#=Rock Creek Trib3,Reach-1,5
Up Type=0
Dn Type=3
Dn Slope=0.005
Boundary for River Rch & Prof#=Rock Creek Trib3,Reach-1,6
Up Type=0
Dn Type=3
Dn Slope=0.005
Boundary for River Rch & Prof#=Rock Creek Trib3,Reach-1,7
Up Type=0
Dn Type=3
Dn Slope=0.005

--- Rock Creek Trib3.g01 (geometry) ---

Geom Title=Existing Conditions

River Reach=Rock Creek Trib3,Reach-1
Reach XY= 30
      1400555.00      6875288.00      1400601.67      6875245.52
      1400615.00      6875249.85      1400648.33      6875278.64
      1400658.33      6875280.14      1400668.33      6875274.41
      1401088.57      6874854.76      1401099.53      6874840.45
      1401104.60      6874822.84      1401108.54      6874689.46
      1401195.19      6874598.51      1401218.91      6874588.67
      1401284.94      6874587.86      1401307.43      6874582.45
      1401401.67      6874496.01      1401414.99      6874499.69
      1401454.91      6874530.23      1401506.65      6874492.44
      1401561.05      6874479.88      1401795.32      6874248.78
      1401811.05      6874240.53      1401857.28      6874232.13
      1401948.98      6874146.18      1402003.57      6874134.11
      1402022.05      6874121.50      1402051.13      6874086.56
      1402060.72      6874035.52      1402094.75      6873998.33
      1402115.52      6873988.66      1402155.00      6873988.00

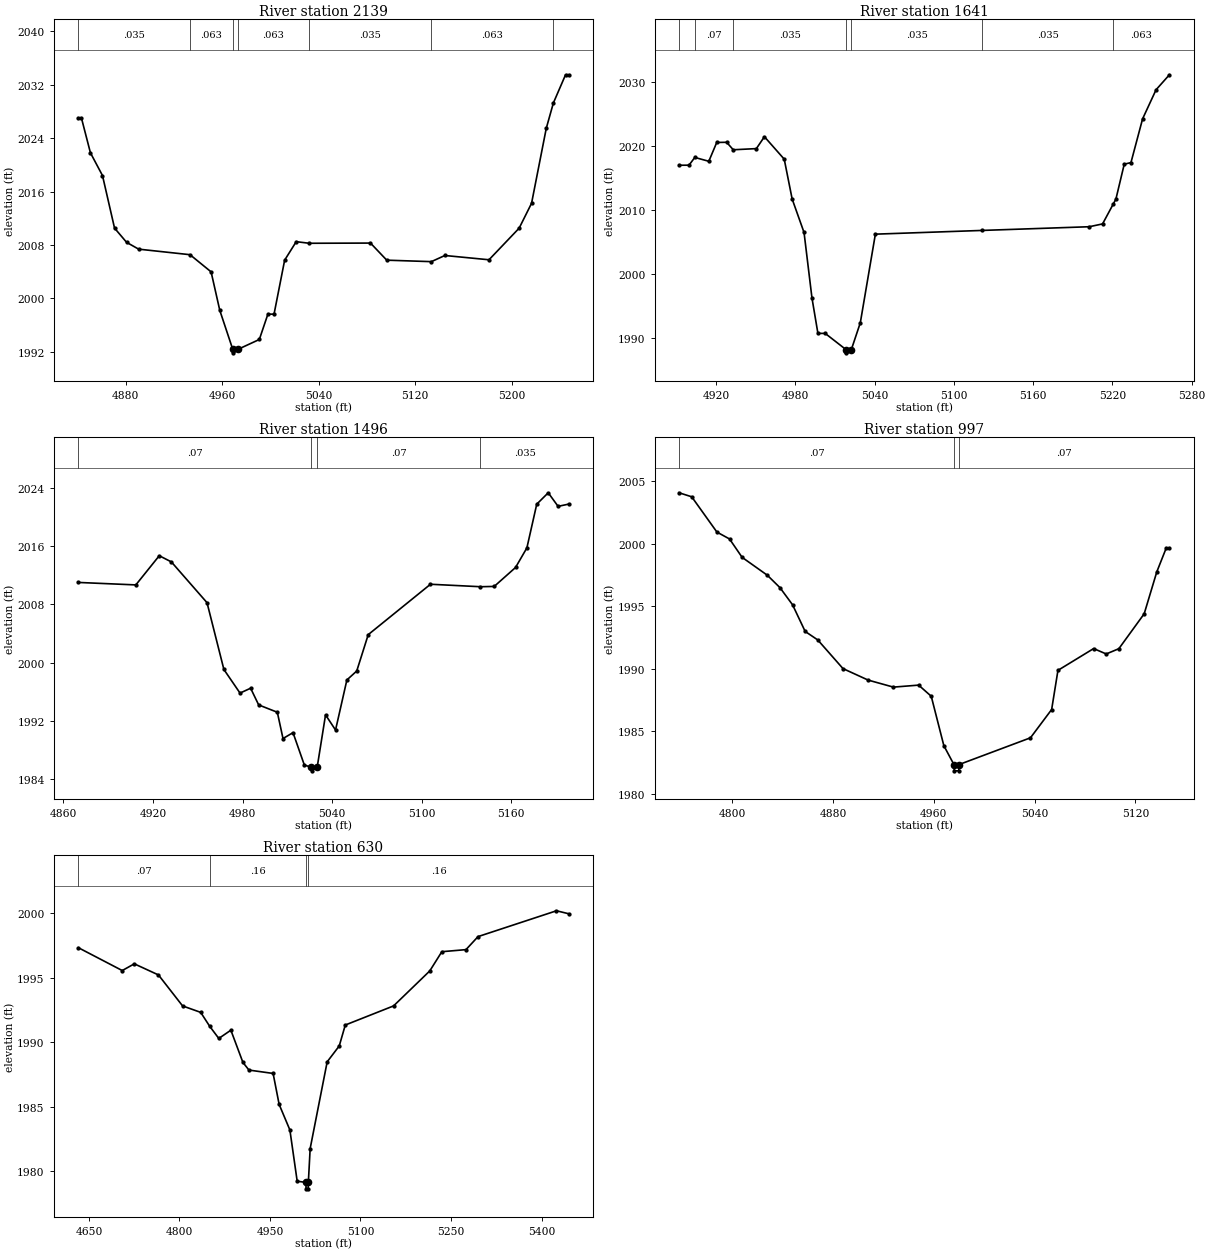
Type RM Length L Ch R = 1,2139,498,498,498
BEGIN DESCRIPTION:
Rock Creek Trib3 3.0
END DESCRIPTION:
XS GIS Cut Line= 3
      1400655.00      6875437.97      1400661.67      6875278.81
      1400605.00      6875037.98
#Sta/Elev= 30
  4840.7 2027.04  4843.2 2027.04  4850.7 2021.80  4860.7 2018.40  4870.7 2010.53
  4880.7 2008.40  4890.7 2007.38  4933.3 2006.55  4950.8 2003.98  4958.0 1998.22
  4968.8 1992.36  4969.0 1991.86  4972.8 1992.36  4990.8 1993.86  4997.9 1997.65
  5003.0 1997.65  5011.8 2005.73  5021.4 2008.50  5032.2 2008.26  5083.0 2008.29
  5096.5 2005.73  5133.5 2005.51  5144.7 2006.43  5181.3 2005.79  5206.3 2010.52
  5216.6 2014.24  5228.8 2025.46  5234.7 2029.26  5244.8 2033.48  5247.4 2033.48
#Mann=7,-1,0
  4840.7   0.035       0  4933.3   0.063       0  4968.8   0.063       0
  4972.8   0.063       0  5032.2   0.035       0  5133.5   0.063       0
  5234.7   0.035       0
Bank Sta=4968.8,4972.8
Exp/Cntr=0.3,0.1

Type RM Length L Ch R = 1,1641,145,145,145
BEGIN DESCRIPTION:
Rock Creek Trib3 2.0
END DESCRIPTION:
XS GIS Cut Line= 3
      1401104.97      6874987.98      1401015.02      6874928.01
      1400754.98      6874888.00
#Sta/Elev= 30
  4891.9 2016.94  4899.4 2016.95  4903.8 2018.16  4914.4 2017.56  4920.4 2020.50
  4927.9 2020.53  4932.9 2019.36  4950.4 2019.54  4956.5 2021.40  4971.5 2017.89
  4977.5 2011.66  4986.5 2006.43  4992.5 1996.19  4997.0 1990.66  5002.5 1990.66
  5018.3 1988.12  5018.5 1987.62  5022.3 1988.12  5029.1 1992.32  5040.5 2006.17
  5121.0 2006.75  5202.4 2007.33  5212.5 2007.77  5220.7 2010.92  5222.6 2011.65
  5228.9 2017.10  5234.0 2017.36  5242.8 2024.19  5253.0 2028.74  5263.1 2031.08
#Mann=7,-1,0
  4891.9   0.035       0  4903.8    0.07       0  4932.9   0.035       0
  5018.3   0.035       0  5022.3   0.035       0  5121.0   0.035       0
  5220.7   0.063       0
Bank Sta=5018.3,5022.3
Exp/Cntr=0.3,0.1

Type RM Length L Ch R = 1,1496,499,499,499
BEGIN DESCRIPTION:
Rock Creek Trib3 1.0
END DESCRIPTION:
XS GIS Cut Line= 3
      1401155.01      6874938.02      1401105.02      6874818.01
      1400955.01      6874688.01
#Sta/Elev= 30
  4870.0 2011.03  4908.5 2010.69  4924.2 2014.71  4932.3 2013.86  4956.2 2008.24
  4967.5 1999.04  4978.3 1995.79  4985.4 1996.46  4990.8 1994.16  5003.3 1993.15
  5007.1 1989.53  5013.8 1990.34  5021.4 1985.88  5026.0 1985.58  5026.3 1985.08
  5030.0 1985.58  5035.6 1992.79  5042.3 1990.70  5049.9 1997.60  5056.5 1998.83
  5064.2 2003.84  5105.9 2010.78  5139.4 2010.44  5148.6 2010.48  5162.9 2013.09
  5170.5 2015.79  5177.1 2021.81  5184.8 2023.38  5191.4 2021.51  5198.5 2021.82
#Mann=4,-1,0
  4870.0    0.07       0  5026.0    0.07       0  5030.0    0.07       0
  5139.4   0.035       0
Bank Sta=5026,5030
Exp/Cntr=0.3,0.1

Type RM Length L Ch R = 1,997,367,367,367
BEGIN DESCRIPTION:
Rock Creek Trib3 1828
END DESCRIPTION:
XS GIS Cut Line= 3
      1401405.00      6874737.99      1401401.67      6874496.01
      1401254.99      6874488.00
#Sta/Elev= 30
  4758.0 2004.06  4768.0 2003.74  4788.0 2000.92  4798.0 2000.37  4808.0 1998.90
  4828.0 1997.47  4838.0 1996.48  4848.0 1995.11  4858.0 1992.98  4868.0 1992.30
  4888.0 1990.01  4908.0 1989.09  4928.0 1988.53  4948.0 1988.69  4958.0 1987.80
  4968.0 1983.85  4976.0 1982.34  4976.3 1981.84  4979.8 1981.84  4980.0 1982.34
  5036.7 1984.48  5053.5 1986.74  5058.5 1989.87  5086.8 1991.61  5096.8 1991.18
  5106.8 1991.60  5126.9 1994.39  5136.9 1997.74  5144.4 1999.65  5146.9 1999.65
#Mann=3,-1,0
  4758.0    0.07       0  4976.0    0.07       0  4980.0    0.07       0
Bank Sta=4976,4980
Exp/Cntr=0.3,0.1

Type RM Length L Ch R = 1,630,0,0,0
BEGIN DESCRIPTION:
Rock Creek Trib3 4130
END DESCRIPTION:
XS GIS Cut Line= 3
      1401696.16      6874720.67      1401689.75      6874353.23
      1401244.82      6874345.71
#Sta/Elev= 30
  4632.5 1997.31  4705.2 1995.54  4725.2 1996.06  4765.2 1995.20  4805.2 1992.80
  4835.2 1992.30  4850.0 1991.23  4865.2 1990.28  4885.2 1990.92  4905.2 1988.42
  4915.2 1987.83  4955.2 1987.57  4965.2 1985.17  4983.0 1983.19  4995.1 1979.22
  5009.6 1979.13  5009.8 1978.63  5013.3 1978.63  5013.6 1979.13  5016.6 1981.75
  5044.8 1988.47  5064.8 1989.70  5074.8 1991.32  5154.8 1992.80  5214.8 1995.51
  5234.8 1997.00  5274.8 1997.16  5294.8 1998.17  5424.8 2000.17  5445.0 1999.94
#Mann=4,-1,0
  4632.5    0.07       0  4850.0    0.16       0  5009.6    0.07       0
  5013.6    0.16       0
Bank Sta=5009.6,5013.6
Exp/Cntr=0.3,0.1

Chan Stop Cuts=-1