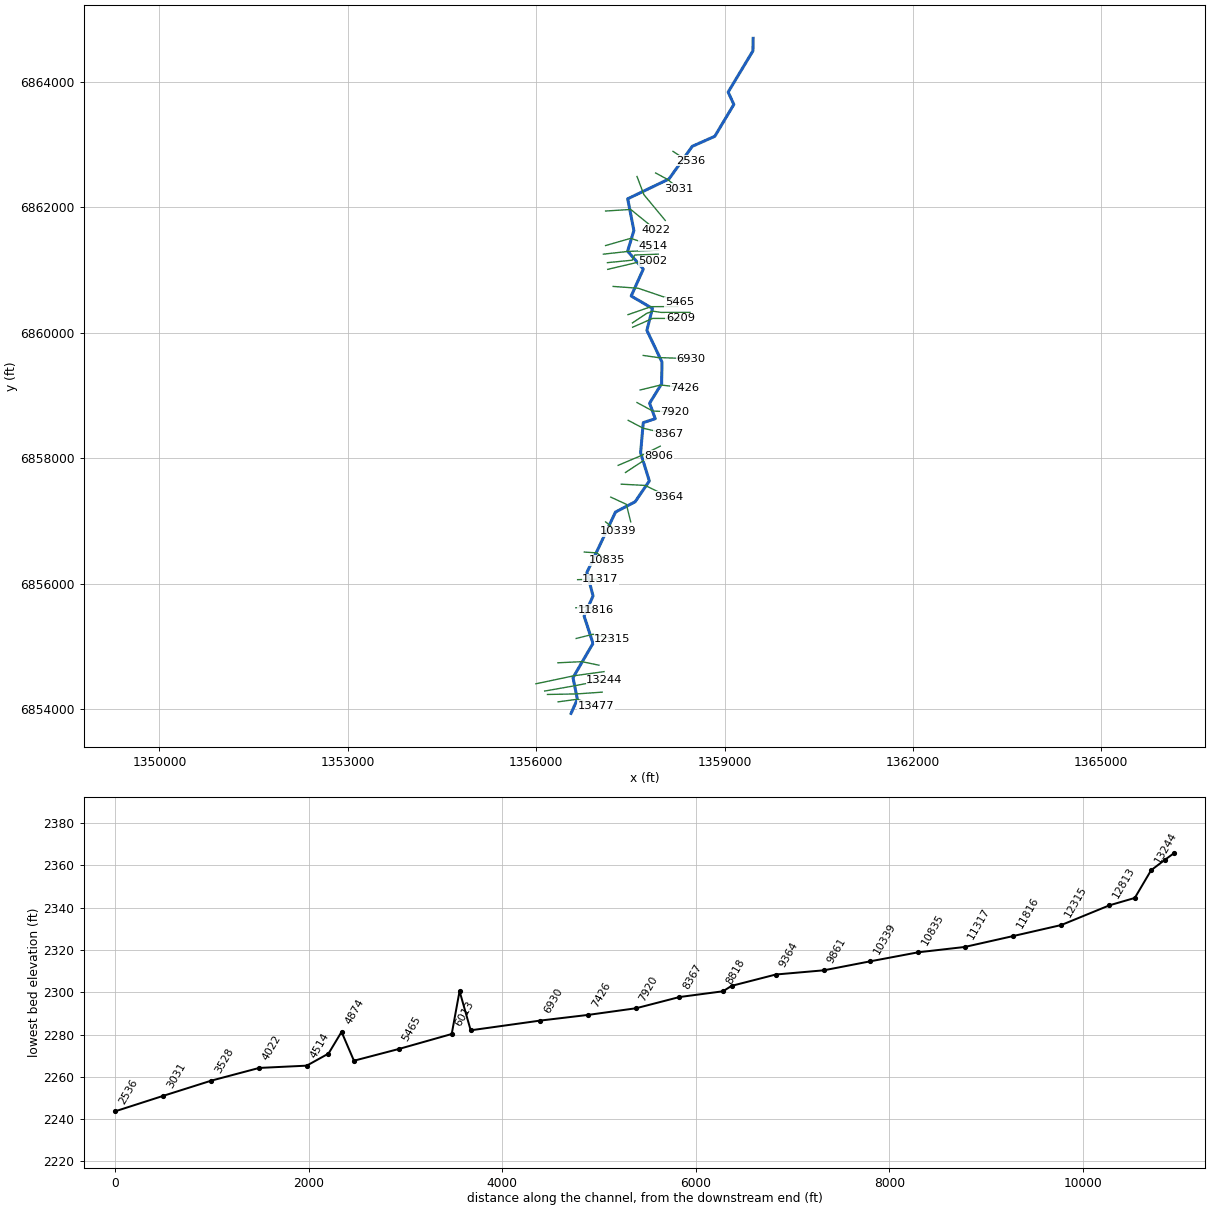
--- Rough Creek Trib1.prj (project) ---

Proj Title=Rough Creek Trib1 Base Level Engineering
Current Plan=p01
Default Exp/Contr=0.3,0.1
English Units
Geom File=g01
Flow File=f01
Plan File=p01
Y Axis Title=Elevation
X Axis Title(PF)=Main Channel Distance
X Axis Title(XS)=Station
BEGIN DESCRIPTION:
Rough Creek Trib1
END DESCRIPTION:
DSS Export Rating Curves= 0
DSS Export Rating Curve Sorted= 0
DSS Export Volume Flow Curves= 0
DXF OffsetX= 0
DXF OffsetY= 0
DXF ScaleX= 1
DXF ScaleY= 10

--- Rough Creek Trib1.p01 (plan) ---

Plan Title=Multiple Run
Short Identifier=Multiple
Geom File=g01
Flow File=f01
Subcritical Flow
K Sum by GR= 0
Std Step Tol= 0.01
Critical Tol= 0.01
Num of Std Step Trials= 20
Max Error Tol= 0.3
Flow Tol Ratio= 0.001
Split Flow NTrial= 30
Split Flow Tol= 0.02
Split Flow Ratio= 0.02
Log Output Level= 0
Friction Slope Method= 1
Unsteady Friction Slope Method= 2
Unsteady Bridges Friction Slope Method= 1
Parabolic Critical Depth
Global Vel Dist=  1 , 1 , 1
Global Log Level= 0
CheckData=True
Encroach Param= -1, 0, 0, 0
BEGIN DESCRIPTION:
Multiple Run
END DESCRIPTION:

--- Rough Creek Trib1.f01 (steady flow) ---

Flow Title=Multiple
Number of Profiles=7
Profile Names=10-year,25-year,50-year,1pct_min,100-year,1pct_plu,500-year
River Rch & RM= Rough Creek Trib,Reach-1,13477
     269     386     484     302     603    1203     949
River Rch & RM= Rough Creek Trib,Reach-1,9364
     423     620     791     501    1000    1996    1623
River Rch & RM= Rough Creek Trib,Reach-1,1586
     452     665     850     540    1078    2151    1758
Boundary for River Rch & Prof#=Rough Creek Trib,Reach-1,1
Up Type=0
Dn Type=3
Dn Slope=0.005
Boundary for River Rch & Prof#=Rough Creek Trib,Reach-1,2
Up Type=0
Dn Type=3
Dn Slope=0.005
Boundary for River Rch & Prof#=Rough Creek Trib,Reach-1,3
Up Type=0
Dn Type=3
Dn Slope=0.005
Boundary for River Rch & Prof#=Rough Creek Trib,Reach-1,4
Up Type=0
Dn Type=3
Dn Slope=0.005
Boundary for River Rch & Prof#=Rough Creek Trib,Reach-1,5
Up Type=0
Dn Type=3
Dn Slope=0.005
Boundary for River Rch & Prof#=Rough Creek Trib,Reach-1,6
Up Type=0
Dn Type=3
Dn Slope=0.005
Boundary for River Rch & Prof#=Rough Creek Trib,Reach-1,7
Up Type=0
Dn Type=3
Dn Slope=0.005

--- Rough Creek Trib1.g01 (geometry) ---

Geom Title=Existing Conditions

River Reach=Rough Creek Trib,Reach-1
Reach XY= 30
      1356555.00      6853938.00      1356655.41      6854163.00
      1356585.98      6854506.91      1356904.49      6855053.21
      1356762.53      6855487.99      1356905.30      6855808.17
      1356807.17      6856182.03      1357262.81      6857144.21
      1357575.04      6857307.36      1357801.53      6857639.50
      1357662.53      6858087.99      1357704.94      6858568.06
      1357896.01      6858630.93      1357805.75      6858877.32
      1357997.47      6859187.99      1358002.94      6859532.14
      1357762.30      6860038.08      1357851.47      6860386.55
      1357512.47      6860584.38      1357705.22      6861013.10
      1357455.93      6861298.48      1357555.45      6861627.81
      1357456.96      6862132.50      1358115.06      6862448.61
      1358484.91      6862968.22      1358844.49      6863128.19
      1359147.23      6863634.59      1359056.79      6863831.89
      1359451.56      6864489.25      1359455.00      6864688.00

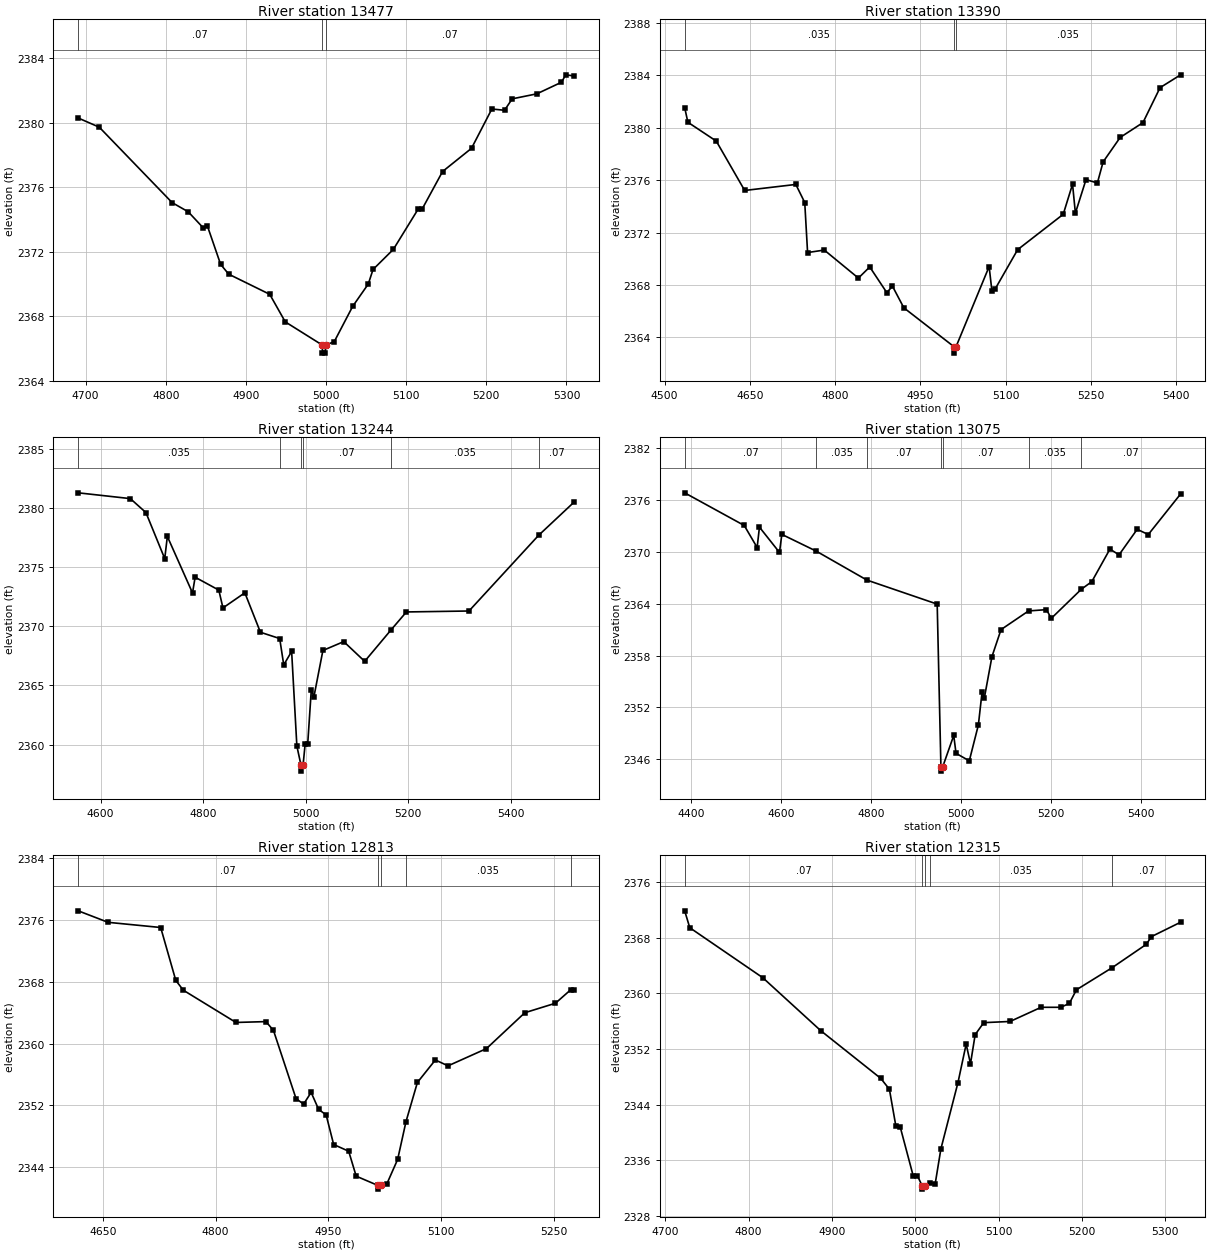
Type RM Length L Ch R = 1,13477,87,87,87
BEGIN DESCRIPTION:
Rough Creek Trib1 27.0
END DESCRIPTION:
XS GIS Cut Line= 3
      1356348.90      6854121.56      1356655.41      6854163.00
      1356946.78      6854058.32
#Sta/Elev= 30
  4690.7 2380.29  4717.0 2379.72  4807.9 2375.04  4828.0 2374.47  4847.0 2373.46
  4852.0 2373.58  4868.4 2371.21  4878.5 2370.60  4929.7 2369.35  4949.1 2367.64
  4995.3 2366.20  4995.5 2365.70  4999.0 2365.70  4999.3 2366.20  5010.2 2366.41
  5033.2 2368.60  5052.7 2369.99  5058.6 2370.89  5084.0 2372.14  5114.7 2374.62
  5120.0 2374.65  5145.4 2376.97  5181.5 2378.41  5206.9 2380.85  5222.7 2380.77
  5232.3 2381.48  5263.0 2381.79  5293.8 2382.51  5299.1 2382.97  5309.6 2382.90
#Mann=3,-1,0
  4690.7    0.07       0  4995.3    0.07       0  4999.3    0.07       0
Bank Sta=4995.3,4999.3
Exp/Cntr=0.3,0.1

Type RM Length L Ch R = 1,13390,146,146,146
BEGIN DESCRIPTION:
Rough Creek Trib1 4019
END DESCRIPTION:
XS GIS Cut Line= 3
      1356179.39      6854239.05      1356644.11      6854247.71
      1357051.11      6854276.18
#Sta/Elev= 30
  4535.2 2381.55  4540.8 2380.43  4590.8 2378.99  4640.8 2375.22  4730.8 2375.68
  4746.5 2374.30  4751.5 2370.48  4780.9 2370.67  4840.9 2368.53  4860.9 2369.38
  4890.9 2367.42  4900.9 2367.91  4920.9 2366.26  5008.9 2363.30  5009.2 2362.80
  5012.9 2363.30  5071.0 2369.41  5076.0 2367.51  5081.1 2367.66  5121.2 2370.70
  5201.4 2373.40  5217.8 2375.70  5222.8 2373.49  5241.5 2376.05  5261.5 2375.79
  5271.6 2377.40  5301.6 2379.27  5341.7 2380.40  5371.8 2383.07  5408.0 2384.05
#Mann=3,-1,0
  4535.2   0.035       0  5008.9   0.035       0  5012.9   0.035       0
Bank Sta=5008.9,5012.9
Exp/Cntr=0.3,0.1

Type RM Length L Ch R = 1,13244,169,169,169
BEGIN DESCRIPTION:
Rough Creek Trib1 4018
END DESCRIPTION:
XS GIS Cut Line= 3
      1356134.86      6854293.57      1356571.66      6854370.39
      1357086.62      6854467.81
#Sta/Elev= 30
  4556.5 2381.30  4658.2 2380.81  4688.6 2379.63  4725.3 2375.73  4730.4 2377.61
  4779.5 2372.83  4784.6 2374.16  4830.8 2373.07  4838.9 2371.56  4881.6 2372.84
  4912.0 2369.50  4949.6 2368.97  4957.5 2366.74  4972.9 2367.88  4983.1 2359.87
  4991.2 2358.25  4991.5 2357.75  4995.2 2358.25  4999.2 2360.02  5004.2 2360.02
  5011.3 2364.65  5016.4 2364.05  5033.9 2367.96  5074.6 2368.71  5115.4 2367.04
  5167.4 2369.73  5196.8 2371.22  5318.9 2371.30  5454.9 2377.71  5524.1 2380.52
#Mann=6,-1,0
  4556.5   0.035       0  4949.6    0.07       0  4991.2    0.07       0
  4995.2    0.07       0  5167.4   0.035       0  5454.9    0.07       0
Bank Sta=4991.2,4995.2
Exp/Cntr=0.3,0.1

Type RM Length L Ch R = 1,13075,262,262,262
BEGIN DESCRIPTION:
Rough Creek Trib1 26.0
END DESCRIPTION:
XS GIS Cut Line= 3
      1355995.41      6854408.98      1356596.81      6854536.15
      1357080.73      6854602.91
#Sta/Elev= 30
  4385.3 2376.84  4517.8 2373.06  4546.5 2370.51  4551.6 2372.87  4596.2 2369.94
  4601.4 2372.03  4678.0 2370.09  4790.7 2366.74  4947.0 2363.96  4955.3 2345.13
  4955.5 2344.63  4959.3 2345.13  4983.8 2348.76  4988.9 2346.69  5018.4 2345.82
  5038.6 2349.97  5046.9 2353.81  5051.9 2353.10  5068.8 2357.88  5089.0 2361.01
  5150.2 2363.17  5190.0 2363.32  5200.8 2362.31  5267.6 2365.68  5290.9 2366.56
  5331.3 2370.33  5351.5 2369.66  5391.9 2372.62  5416.5 2372.01  5488.5 2376.71
#Mann=7,-1,0
  4385.3    0.07       0  4678.0   0.035       0  4790.7    0.07       0
  4955.3    0.07       0  4959.3    0.07       0  5150.2   0.035       0
  5267.6    0.07       0
Bank Sta=4955.3,4959.3
Exp/Cntr=0.3,0.1

Type RM Length L Ch R = 1,12813,498,498,498
BEGIN DESCRIPTION:
Rough Creek Trib1 25.0
END DESCRIPTION:
XS GIS Cut Line= 3
      1356345.27      6854743.50      1356727.75      6854761.44
      1356999.38      6854705.16
#Sta/Elev= 30
  4617.1 2377.20  4656.9 2375.71  4726.9 2375.04  4747.0 2368.19  4757.0 2366.92
  4827.1 2362.74  4867.1 2362.85  4877.1 2361.70  4907.1 2352.88  4917.2 2352.16
  4927.2 2353.68  4937.2 2351.48  4947.2 2350.76  4957.2 2346.93  4977.2 2346.06
  4987.2 2342.83  5015.6 2341.65  5015.9 2341.15  5019.6 2341.65  5027.8 2341.78
  5042.4 2345.00  5053.5 2349.89  5068.7 2354.97  5092.6 2357.88  5109.5 2357.12
  5160.6 2359.35  5211.7 2364.00  5252.5 2365.23  5273.0 2366.99  5277.4 2366.99
#Mann=5,-1,0
  4617.1    0.07       0  5015.6    0.07       0  5019.6    0.07       0
  5053.5   0.035       0  5273.0    0.07       0
Bank Sta=5015.6,5019.6
Exp/Cntr=0.3,0.1

Type RM Length L Ch R = 1,12315,499,499,499
BEGIN DESCRIPTION:
Rough Creek Trib1 24.0
END DESCRIPTION:
XS GIS Cut Line= 3
      1356636.71      6855130.86      1356905.12      6855198.05
      1357214.96      6855125.14
#Sta/Elev= 30
  4723.3 2371.89  4729.4 2369.46  4817.0 2362.26  4886.5 2354.64  4958.6 2347.76
  4968.9 2346.20  4976.7 2340.88  4981.8 2340.81  4997.4 2333.76  5002.5 2333.76
  5008.1 2332.32  5008.4 2331.82  5012.1 2332.32  5018.1 2332.77  5023.8 2332.55
  5030.7 2337.62  5051.2 2347.17  5061.0 2352.70  5066.2 2349.87  5071.8 2354.06
  5082.1 2355.79  5113.7 2355.96  5150.9 2358.00  5174.5 2358.00  5184.8 2358.56
  5193.3 2360.52  5236.1 2363.70  5277.2 2367.07  5283.2 2368.17  5318.3 2370.25
#Mann=5,-1,0
  4723.3    0.07       0  5008.1    0.07       0  5012.1    0.07       0
  5018.1   0.035       0  5236.1    0.07       0
Bank Sta=5008.1,5012.1
Exp/Cntr=0.3,0.1

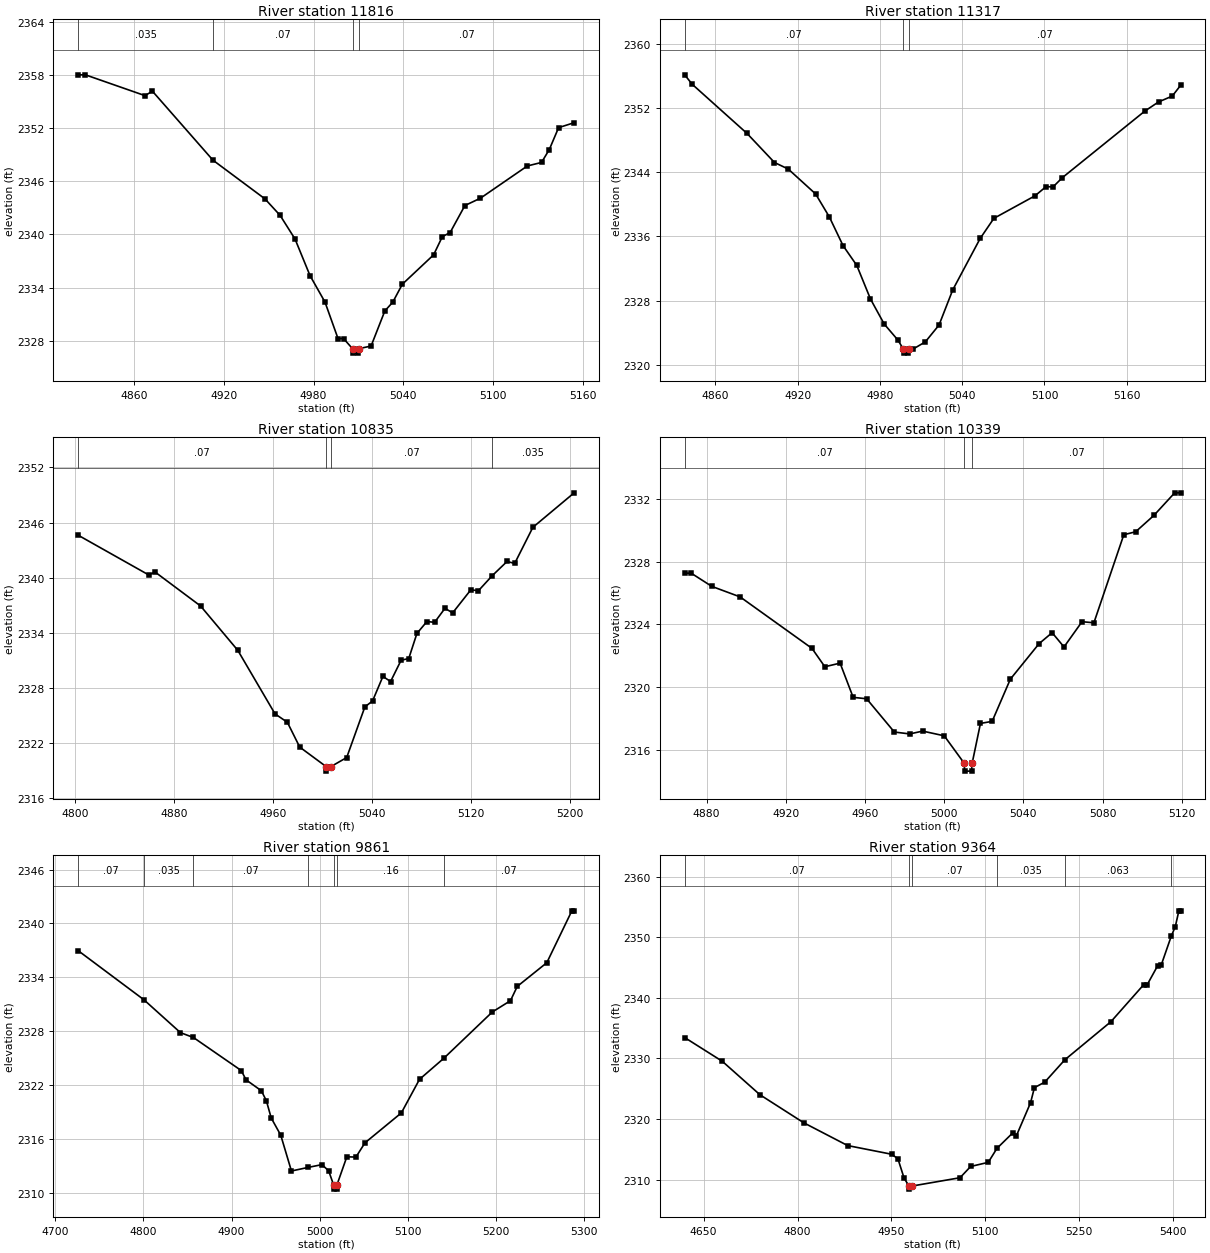
Type RM Length L Ch R = 1,11816,499,499,499
BEGIN DESCRIPTION:
Rough Creek Trib1 23.0
END DESCRIPTION:
XS GIS Cut Line= 3
      1356630.47      6855619.50      1356807.33      6855632.03
      1356955.00      6855588.00
#Sta/Elev= 30
  4822.7 2358.04  4827.5 2358.04  4867.3 2355.69  4872.3 2356.19  4912.7 2348.40
  4947.5 2344.02  4957.6 2342.16  4967.6 2339.48  4977.6 2335.35  4987.6 2332.36
  4996.3 2328.24  5000.0 2328.24  5006.0 2327.09  5006.3 2326.59  5009.8 2326.59
  5010.0 2327.09  5018.4 2327.39  5027.6 2331.36  5032.9 2332.35  5039.3 2334.38
  5060.2 2337.70  5066.0 2339.75  5071.2 2340.21  5081.1 2343.27  5091.5 2344.10
  5122.8 2347.74  5132.3 2348.14  5137.5 2349.60  5143.7 2352.07  5154.1 2352.63
#Mann=4,-1,0
  4822.7   0.035       0  4912.7    0.07       0  5006.0    0.07       0
  5010.0    0.07       0
Bank Sta=5006,5010
Exp/Cntr=0.3,0.1

Type RM Length L Ch R = 1,11317,482,482,482
BEGIN DESCRIPTION:
Rough Creek Trib1 22.0
END DESCRIPTION:
XS GIS Cut Line= 3
      1356659.51      6856067.43      1356821.87      6856071.44
      1357021.14      6856074.42
#Sta/Elev= 30
  4837.6 2356.14  4843.1 2354.96  4883.1 2348.83  4903.1 2345.21  4913.1 2344.40
  4933.1 2341.29  4943.1 2338.43  4953.1 2334.85  4963.1 2332.39  4973.1 2328.20
  4983.1 2325.08  4993.1 2323.08  4997.1 2321.95  4997.3 2321.45  5000.8 2321.45
  5001.1 2321.95  5004.1 2321.95  5013.1 2322.85  5023.1 2324.95  5033.1 2329.33
  5053.1 2335.74  5063.1 2338.25  5093.1 2341.06  5101.2 2342.21  5106.2 2342.16
  5113.1 2343.33  5173.2 2351.62  5183.2 2352.76  5193.2 2353.49  5199.3 2354.83
#Mann=3,-1,0
  4837.6    0.07       0  4997.1    0.07       0  5001.1    0.07       0
Bank Sta=4997.1,5001.1
Exp/Cntr=0.3,0.1

Type RM Length L Ch R = 1,10835,496,496,496
BEGIN DESCRIPTION:
Rough Creek Trib1 21.0
END DESCRIPTION:
XS GIS Cut Line= 3
      1356766.17      6856506.98      1356963.44      6856493.93
      1357127.68      6856373.78
#Sta/Elev= 30
  4802.3 2344.62  4859.4 2340.29  4864.4 2340.62  4901.3 2336.91  4931.4 2332.08
  4961.5 2325.16  4971.5 2324.24  4981.5 2321.54  5002.8 2319.42  5003.1 2318.92
  5006.8 2319.42  5019.5 2320.40  5034.2 2325.92  5040.4 2326.56  5048.8 2329.24
  5055.0 2328.68  5063.5 2331.00  5069.7 2331.19  5076.3 2333.92  5084.4 2335.22
  5090.6 2335.13  5099.0 2336.66  5105.2 2336.16  5119.9 2338.67  5126.1 2338.58
  5137.2 2340.21  5149.2 2341.76  5155.4 2341.55  5170.1 2345.48  5203.5 2349.24
#Mann=4,-1,0
  4802.3    0.07       0  5002.8    0.07       0  5006.8    0.07       0
  5137.2   0.035       0
Bank Sta=5002.8,5006.8
Exp/Cntr=0.3,0.1

Type RM Length L Ch R = 1,10339,478,478,478
BEGIN DESCRIPTION:
Rough Creek Trib1 20.0
END DESCRIPTION:
XS GIS Cut Line= 3
      1357105.00      6856988.00      1357204.87      6856903.06
      1357304.99      6856838.01
#Sta/Elev= 30
  4868.9 2327.26  4872.2 2327.26  4882.6 2326.42  4896.9 2325.75  4933.2 2322.47
  4939.7 2321.30  4947.4 2321.53  4954.0 2319.35  4960.8 2319.26  4974.8 2317.14
  4982.6 2317.02  4989.1 2317.20  5000.0 2316.90  5010.1 2315.15  5010.3 2314.65
  5013.8 2314.65  5014.1 2315.15  5018.3 2317.69  5024.2 2317.82  5033.4 2320.51
  5047.9 2322.77  5054.5 2323.47  5060.5 2322.56  5069.6 2324.17  5075.6 2324.10
  5090.7 2329.71  5096.7 2329.90  5105.9 2330.94  5116.4 2332.38  5119.4 2332.38
#Mann=3,-1,0
  4868.9    0.07       0  5010.1    0.07       0  5014.1    0.07       0
Bank Sta=5010.1,5014.1
Exp/Cntr=0.3,0.1

Type RM Length L Ch R = 1,9861,497,497,497
BEGIN DESCRIPTION:
Rough Creek Trib1 19.0
END DESCRIPTION:
XS GIS Cut Line= 3
      1357186.40      6857382.16      1357435.16      6857267.77
      1357505.01      6856987.96
#Sta/Elev= 30
  4726.2 2336.97  4800.6 2331.51  4842.1 2327.84  4856.8 2327.30  4911.0 2323.62
  4916.5 2322.58  4933.8 2321.37  4939.5 2320.25  4945.0 2318.33  4955.8 2316.42
  4967.9 2312.43  4986.4 2312.82  5002.5 2313.14  5010.1 2312.45  5015.6 2310.91
  5015.9 2310.41  5019.4 2310.41  5019.6 2310.91  5030.7 2314.01  5041.0 2313.98
  5051.3 2315.57  5092.5 2318.90  5113.1 2322.64  5140.6 2324.98  5195.6 2330.14
  5216.2 2331.40  5223.9 2332.99  5257.4 2335.63  5285.8 2341.41  5288.4 2341.41
#Mann=7,-1,0
  4726.2    0.07       0  4800.6   0.035       0  4856.8    0.07       0
  4986.4    0.16       0  5015.6    0.07       0  5019.6    0.16       0
  5140.6    0.07       0
Bank Sta=5015.6,5019.6
Exp/Cntr=0.3,0.1

Type RM Length L Ch R = 1,9364,458,458,458
BEGIN DESCRIPTION:
Rough Creek Trib1 18.0
END DESCRIPTION:
XS GIS Cut Line= 3
      1357355.01      6857588.00      1357734.69      6857568.13
      1358105.01      6857388.00
#Sta/Elev= 30
  4619.8 2333.44  4679.9 2329.52  4740.0 2324.00  4810.0 2319.37  4880.1 2315.61
  4950.2 2314.18  4960.3 2313.44  4970.3 2310.20  4978.2 2308.92  4978.5 2308.42
  4982.3 2308.92  5059.5 2310.30  5076.5 2312.16  5104.6 2312.84  5118.5 2315.15
  5144.1 2317.74  5149.7 2317.27  5172.2 2322.69  5178.3 2325.17  5194.8 2326.08
  5226.8 2329.76  5300.6 2336.07  5352.6 2342.14  5358.2 2342.12  5375.2 2345.31
  5380.7 2345.37  5396.9 2350.19  5403.3 2351.75  5409.0 2354.36  5411.8 2354.36
#Mann=6,-1,0
  4619.8    0.07       0  4978.2    0.07       0  4982.3    0.07       0
  5118.5   0.035       0  5226.8   0.063       0  5396.9   0.035       0
Bank Sta=4978.2,4982.3
Exp/Cntr=0.3,0.1

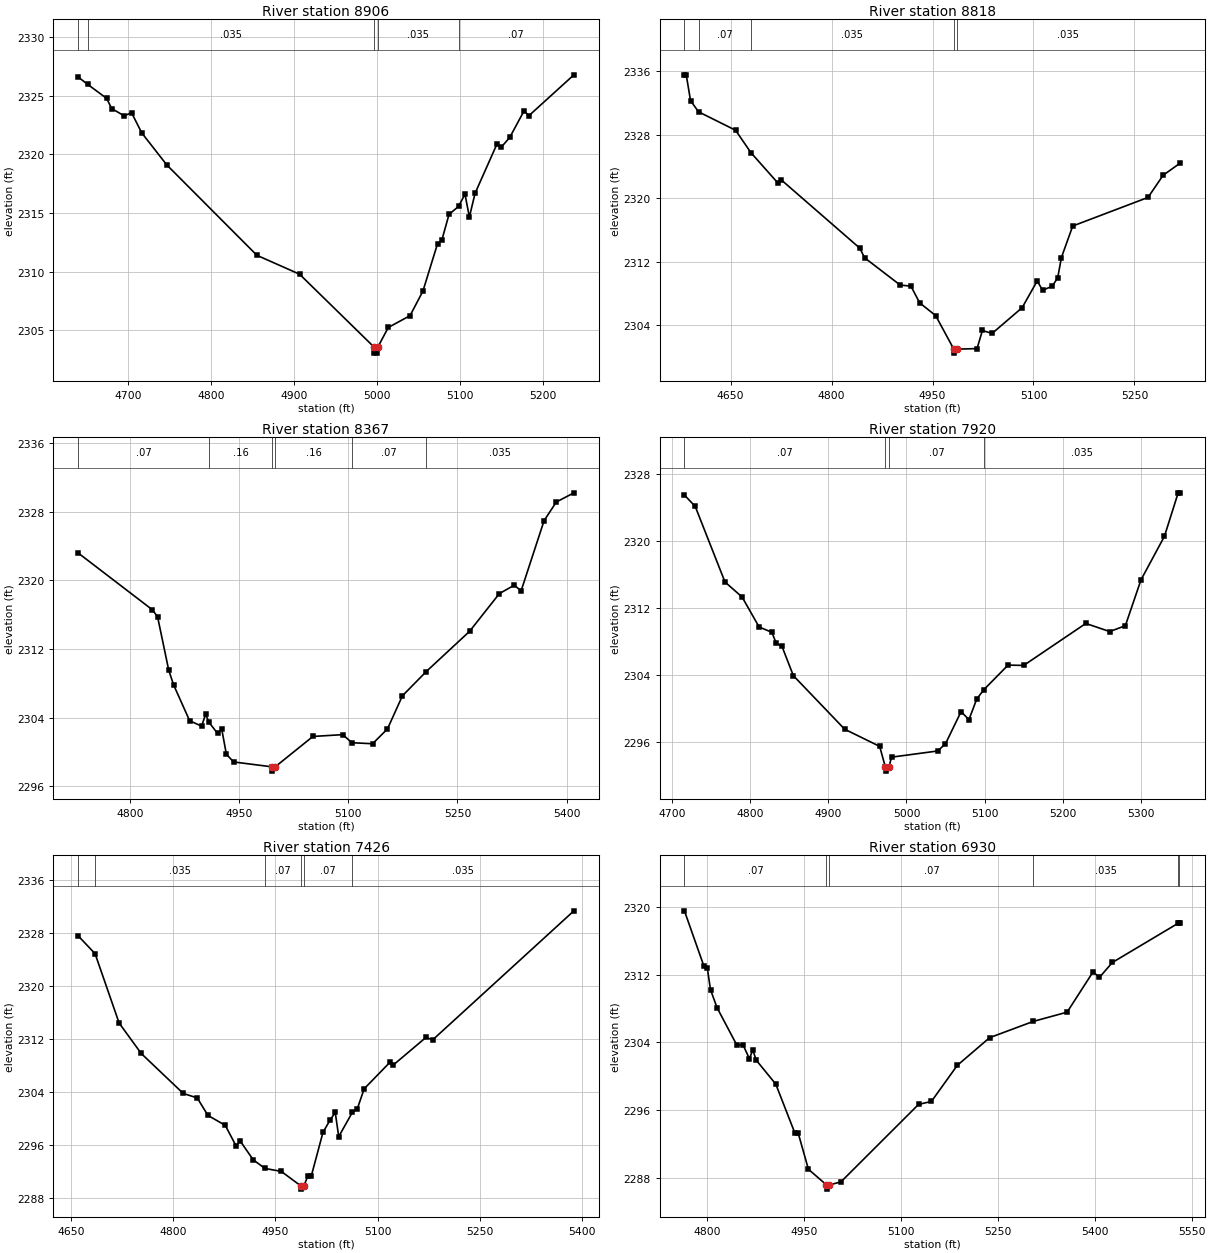
Type RM Length L Ch R = 1,8906,88,88,88
BEGIN DESCRIPTION:
Rough Creek Trib1 4017
END DESCRIPTION:
XS GIS Cut Line= 3
      1357421.31      6857774.26      1357722.09      6857971.52
      1357948.98      6858039.66
#Sta/Elev= 30
  4640.3 2326.61  4651.6 2325.99  4674.5 2324.79  4680.6 2323.92  4695.6 2323.30
  4704.5 2323.57  4716.7 2321.85  4746.9 2319.11  4855.4 2311.39  4906.7 2309.78
  4996.6 2303.54  4996.9 2303.04  5000.5 2303.04  5000.8 2303.54  5013.5 2305.23
  5039.7 2306.24  5055.2 2308.34  5072.8 2312.39  5078.0 2312.70  5086.6 2314.89
  5098.0 2315.56  5105.8 2316.61  5111.1 2314.66  5117.9 2316.68  5144.1 2320.86
  5149.3 2320.61  5159.7 2321.46  5177.1 2323.75  5182.4 2323.29  5236.9 2326.80
#Mann=5,-1,0
  4640.3    0.07       0  4651.6   0.035       0  4996.6   0.035       0
  5000.8   0.035       0  5098.0    0.07       0
Bank Sta=4996.6,5000.8
Exp/Cntr=0.3,0.1

Type RM Length L Ch R = 1,8818,451,451,451
BEGIN DESCRIPTION:
Rough Creek Trib1 17.0
END DESCRIPTION:
XS GIS Cut Line= 3
      1357304.98      6857887.99      1357690.56      6858051.20
      1357975.03      6858193.12
#Sta/Elev= 30
  4581.3 2335.54  4584.0 2335.54  4590.4 2332.29  4602.3 2330.88  4657.3 2328.56
  4680.1 2325.74  4719.7 2321.96  4725.2 2322.31  4841.9 2313.71  4849.0 2312.50
  4901.8 2309.07  4917.9 2308.92  4930.9 2306.82  4954.6 2305.22  4981.6 2300.99
  4981.9 2300.49  4985.8 2300.99  5016.1 2301.06  5024.1 2303.34  5038.5 2302.97
  5083.2 2306.22  5105.5 2309.58  5113.6 2308.41  5127.9 2308.92  5136.0 2309.99
  5141.5 2312.53  5158.3 2316.50  5270.2 2320.10  5292.6 2322.89  5317.9 2324.42
#Mann=5,-1,0
  4581.3   0.035       0  4602.3    0.07       0  4680.1   0.035       0
  4981.6   0.035       0  4985.8   0.035       0
Bank Sta=4981.6,4985.8
Exp/Cntr=0.3,0.1

Type RM Length L Ch R = 1,8367,447,447,447
BEGIN DESCRIPTION:
Rough Creek Trib1 16.0
END DESCRIPTION:
XS GIS Cut Line= 3
      1357464.85      6858604.64      1357704.93      6858478.07
      1358105.01      6858388.00
#Sta/Elev= 30
  4728.6 2323.17  4830.5 2316.56  4837.7 2315.75  4853.1 2309.50  4859.8 2307.80
  4881.8 2303.63  4898.2 2303.00  4903.8 2304.38  4908.3 2303.46  4920.2 2302.15
  4925.9 2302.67  4932.3 2299.73  4942.2 2298.83  4995.0 2298.26  4995.3 2297.76
  4999.4 2298.26  5051.3 2301.80  5092.3 2302.01  5104.9 2301.07  5133.3 2300.95
  5153.8 2302.68  5174.3 2306.53  5207.1 2309.36  5266.6 2314.04  5307.6 2318.44
  5328.1 2319.42  5337.5 2318.76  5369.1 2326.94  5385.9 2329.11  5410.1 2330.18
#Mann=6,-1,0
  4728.6    0.07       0  4908.3    0.16       0  4995.0    0.07       0
  4999.4    0.16       0  5104.9    0.07       0  5207.1   0.035       0
Bank Sta=4995,4999.4
Exp/Cntr=0.3,0.1

Type RM Length L Ch R = 1,7920,494,494,494
BEGIN DESCRIPTION:
Rough Creek Trib1 15.0
END DESCRIPTION:
XS GIS Cut Line= 3
      1357605.03      6858887.98      1357855.16      6858753.06
      1358205.04      6858738.00
#Sta/Elev= 30
  4715.8 2325.48  4729.6 2324.13  4767.7 2315.09  4789.6 2313.29  4811.4 2309.71
  4827.7 2309.07  4833.3 2307.76  4840.7 2307.38  4855.2 2303.89  4920.9 2297.48
  4965.7 2295.43  4972.9 2292.97  4973.3 2292.47  4977.5 2292.97  4980.9 2294.14
  5039.9 2294.88  5049.9 2295.74  5069.9 2299.59  5079.9 2298.62  5089.9 2301.09
  5099.1 2302.22  5130.0 2305.15  5150.0 2305.11  5229.5 2310.13  5260.1 2309.16
  5280.1 2309.86  5300.1 2315.34  5330.1 2320.55  5347.7 2325.75  5350.2 2325.75
#Mann=4,-1,0
  4715.8    0.07       0  4972.9    0.07       0  4977.5    0.07       0
  5099.1   0.035       0
Bank Sta=4972.9,4977.5
Exp/Cntr=0.3,0.1

Type RM Length L Ch R = 1,7426,496,496,496
BEGIN DESCRIPTION:
Rough Creek Trib1 14.0
END DESCRIPTION:
XS GIS Cut Line= 3
      1357655.00      6859088.00      1357985.32      6859168.13
      1358370.74      6859119.23
#Sta/Elev= 30
  4660.1 2327.62  4684.9 2324.93  4720.2 2314.45  4752.7 2309.84  4814.4 2303.80
  4835.0 2303.12  4850.7 2300.48  4876.2 2298.97  4892.5 2295.78  4897.7 2296.67
  4917.3 2293.76  4934.5 2292.46  4958.5 2292.01  4987.1 2289.83  4987.4 2289.33
  4991.7 2289.83  4997.3 2291.24  5002.4 2291.24  5019.8 2297.92  5029.9 2299.72
  5037.8 2300.93  5042.9 2297.27  5062.9 2300.93  5070.2 2301.47  5080.3 2304.50
  5117.9 2308.48  5122.9 2308.08  5171.0 2312.26  5181.1 2311.91  5388.5 2331.41
#Mann=6,-1,0
  4660.1    0.07       0  4684.9   0.035       0  4934.5    0.07       0
  4987.1    0.07       0  4991.7    0.07       0  5062.9   0.035       0
Bank Sta=4987.1,4991.7
Exp/Cntr=0.3,0.1

Type RM Length L Ch R = 1,6930,721,721,721
BEGIN DESCRIPTION:
Rough Creek Trib1 13.0
END DESCRIPTION:
XS GIS Cut Line= 3
      1357704.96      6859638.01      1357937.97      6859604.52
      1358469.87      6859586.55
#Sta/Elev= 30
  4764.6 2319.57  4794.8 2313.02  4799.9 2312.86  4805.0 2310.24  4815.1 2308.11
  4845.5 2303.72  4855.6 2303.67  4865.3 2302.06  4870.4 2303.12  4875.8 2301.90
  4906.1 2299.06  4935.8 2293.24  4940.9 2293.24  4956.6 2288.99  4984.6 2287.14
  4984.9 2286.64  4989.2 2287.14  5007.0 2287.50  5127.1 2296.66  5147.1 2297.02
  5187.1 2301.28  5237.2 2304.56  5305.0 2306.49  5357.2 2307.58  5397.3 2312.34
  5407.3 2311.70  5427.3 2313.46  5529.6 2318.12  5530.2 2318.12  5532.2 2318.12
#Mann=6,-1,0
  4764.6    0.07       0  4984.6    0.07       0  4989.2    0.07       0
  5305.0   0.035       0  5529.6    0.07       0  5530.2   0.035       0
Bank Sta=4984.6,4989.2
Exp/Cntr=0.3,0.1

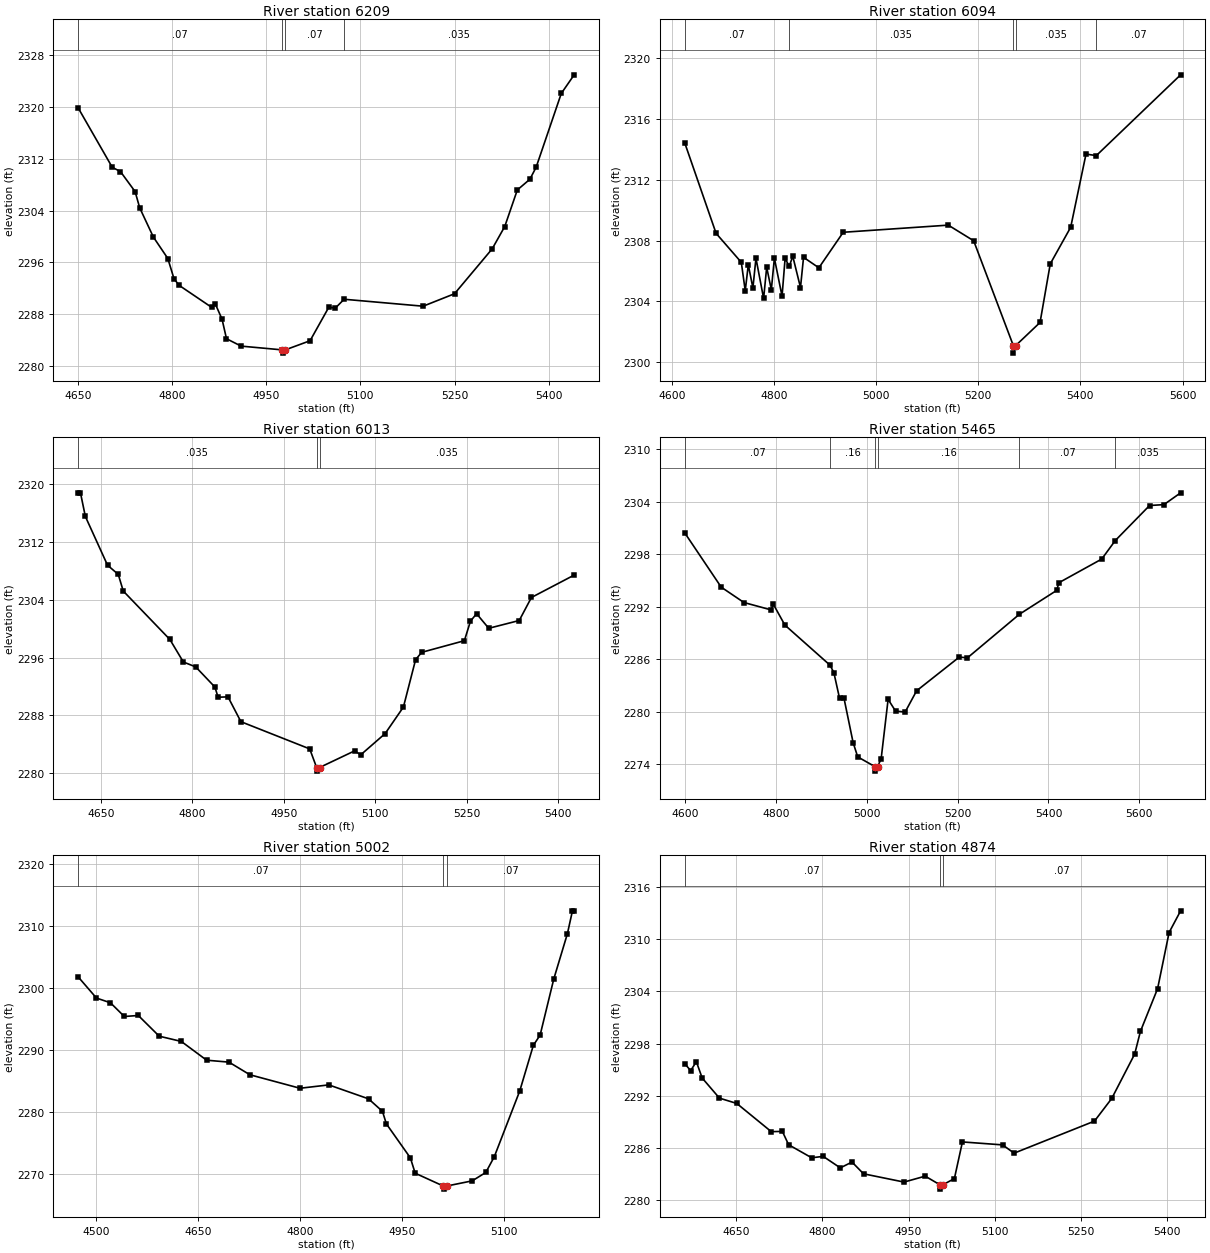
Type RM Length L Ch R = 1,6209,115,115,115
BEGIN DESCRIPTION:
Rough Creek Trib1 12.0
END DESCRIPTION:
XS GIS Cut Line= 3
      1357535.41      6860087.27      1357855.12      6860227.95
      1358295.52      6860227.06
#Sta/Elev= 30
  4650.7 2319.80  4704.9 2310.66  4717.9 2310.01  4741.3 2306.92  4748.6 2304.42
  4770.4 2299.91  4793.4 2296.61  4803.2 2293.50  4811.3 2292.48  4863.4 2289.07
  4868.9 2289.63  4879.7 2287.27  4886.8 2284.25  4910.1 2283.11  4975.6 2282.53
  4976.0 2282.03  4980.4 2282.53  5019.9 2283.94  5049.9 2289.13  5059.9 2288.95
  5074.1 2290.33  5199.9 2289.26  5249.9 2291.18  5309.9 2298.10  5329.9 2301.54
  5349.9 2307.17  5369.9 2308.82  5379.9 2310.68  5419.9 2322.04  5440.4 2324.91
#Mann=4,-1,0
  4650.7    0.07       0  4975.6    0.07       0  4980.4    0.07       0
  5074.1   0.035       0
Bank Sta=4975.6,4980.4
Exp/Cntr=0.3,0.1

Type RM Length L Ch R = 1,6094,81,81,81
BEGIN DESCRIPTION:
Rough Creek Trib1 4138
END DESCRIPTION:
XS GIS Cut Line= 5
      1357532.72      6860156.30      1357760.55      6860308.19
      1357855.48      6860343.20      1357990.59      6860323.38
      1358450.33      6860323.38
#Sta/Elev= 30
  4625.0 2314.45  4686.5 2308.48  4735.9 2306.57  4743.6 2304.70  4749.6 2306.41
  4758.6 2304.88  4764.6 2306.84  4779.6 2304.19  4785.6 2306.24  4794.7 2304.77
  4800.7 2306.84  4815.7 2304.34  4821.7 2306.84  4829.7 2306.30  4836.7 2306.97
  4851.8 2304.91  4857.8 2306.90  4887.8 2306.21  4935.5 2308.55  5141.3 2309.02
  5191.0 2307.99  5268.6 2301.09  5268.9 2300.59  5273.4 2301.09  5321.0 2302.61
  5341.0 2306.47  5381.0 2308.88  5411.0 2313.70  5431.2 2313.60  5596.3 2318.92
#Mann=5,-1,0
  4625.0    0.07       0  4829.7   0.035       0  5268.6   0.035       0
  5273.4   0.035       0  5431.2    0.07       0
Bank Sta=5268.6,5273.4
Exp/Cntr=0.3,0.1

Type RM Length L Ch R = 1,6013,548,548,548
BEGIN DESCRIPTION:
Rough Creek Trib1 11.0
END DESCRIPTION:
XS GIS Cut Line= 3
      1357462.92      6860287.80      1357828.86      6860414.94
      1358255.06      6860416.57
#Sta/Elev= 30
  4612.6 2318.84  4616.3 2318.84  4624.3 2315.57  4660.7 2308.81  4678.3 2307.54
  4686.5 2305.23  4763.0 2298.52  4785.1 2295.40  4805.4 2294.72  4836.8 2291.93
  4842.1 2290.52  4858.3 2290.57  4879.5 2287.13  4992.4 2283.36  5003.7 2280.78
  5004.1 2280.28  5008.5 2280.78  5066.1 2283.09  5076.1 2282.54  5116.1 2285.48
  5146.1 2289.16  5166.1 2295.73  5176.1 2296.74  5246.1 2298.35  5256.1 2301.06
  5266.1 2302.09  5286.1 2300.07  5336.1 2301.15  5356.1 2304.34  5426.2 2307.44
#Mann=3,-1,0
  4612.6   0.035       0  5003.7   0.035       0  5008.5   0.035       0
Bank Sta=5003.7,5008.5
Exp/Cntr=0.3,0.1

Type RM Length L Ch R = 1,5465,463,463,463
BEGIN DESCRIPTION:
Rough Creek Trib1 10.0
END DESCRIPTION:
XS GIS Cut Line= 3
      1357224.76      6860737.30      1357625.38      6860707.84
      1358279.80      6860485.37
#Sta/Elev= 30
  4598.3 2300.45  4678.8 2294.23  4728.9 2292.47  4788.6 2291.63  4793.7 2292.27
  4819.1 2289.89  4918.6 2285.30  4927.0 2284.46  4939.5 2281.53  4949.5 2281.49
  4969.5 2276.44  4979.6 2274.81  5018.2 2273.68  5018.6 2273.18  5023.3 2273.68
  5031.3 2274.61  5046.6 2281.39  5063.0 2280.05  5084.1 2279.94  5109.4 2282.37
  5203.5 2286.23  5221.4 2286.14  5336.0 2291.13  5417.9 2293.85  5423.1 2294.74
  5517.3 2297.44  5547.2 2299.56  5622.8 2303.57  5654.4 2303.67  5691.2 2305.02
#Mann=6,-1,0
  4598.3    0.07       0  4918.6    0.16       0  5018.2    0.07       0
  5023.3    0.16       0  5336.0    0.07       0  5547.2   0.035       0
Bank Sta=5018.2,5023.3
Exp/Cntr=0.3,0.1

Type RM Length L Ch R = 1,5002,128,128,128
BEGIN DESCRIPTION:
Rough Creek Trib1 9.0
END DESCRIPTION:
XS GIS Cut Line= 3
      1357138.86      6861009.04      1357651.49      6861129.52
      1357855.01      6861138.00
#Sta/Elev= 30
  4473.4 2301.76  4500.3 2298.36  4520.8 2297.61  4541.3 2295.40  4561.9 2295.56
  4592.7 2292.23  4625.2 2291.39  4662.5 2288.37  4695.4 2288.06  4726.2 2286.03
  4800.0 2283.86  4842.4 2284.40  4900.9 2282.16  4921.4 2280.15  4927.2 2278.13
  4962.5 2272.67  4969.6 2270.20  5011.0 2268.14  5011.4 2267.64  5016.1 2268.14
  5053.6 2268.97  5073.6 2270.32  5086.1 2272.85  5123.6 2283.43  5143.6 2290.76
  5153.6 2292.41  5173.7 2301.43  5193.7 2308.69  5201.2 2312.39  5203.7 2312.39
#Mann=3,-1,0
  4473.4    0.07       0  5011.0    0.07       0  5016.1    0.07       0
Bank Sta=5011,5016.1
Exp/Cntr=0.3,0.1

Type RM Length L Ch R = 1,4874,135,135,135
BEGIN DESCRIPTION:
Rough Creek Trib1 4137
END DESCRIPTION:
XS GIS Cut Line= 4
      1357134.69      6861115.82      1357527.74      6861154.71
      1357567.32      6861237.35      1357945.07      6861251.24
#Sta/Elev= 30
  4559.8 2295.71  4570.2 2294.90  4580.2 2295.92  4590.3 2294.05  4620.4 2291.74
  4650.6 2291.13  4710.8 2287.89  4730.1 2287.92  4741.0 2286.39  4781.2 2284.89
  4801.3 2285.05  4831.1 2283.73  4851.5 2284.40  4871.6 2283.05  4942.2 2282.10
  4979.1 2282.78  5004.8 2281.79  5005.2 2281.29  5009.9 2281.79  5030.0 2282.50
  5044.0 2286.71  5114.1 2286.37  5134.1 2285.42  5274.2 2289.10  5304.3 2291.70
  5344.3 2296.80  5354.3 2299.40  5384.3 2304.32  5404.3 2310.76  5424.4 2313.25
#Mann=3,-1,0
  4559.8    0.07       0  5004.8    0.07       0  5009.9    0.07       0
Bank Sta=5004.8,5009.9
Exp/Cntr=0.3,0.1

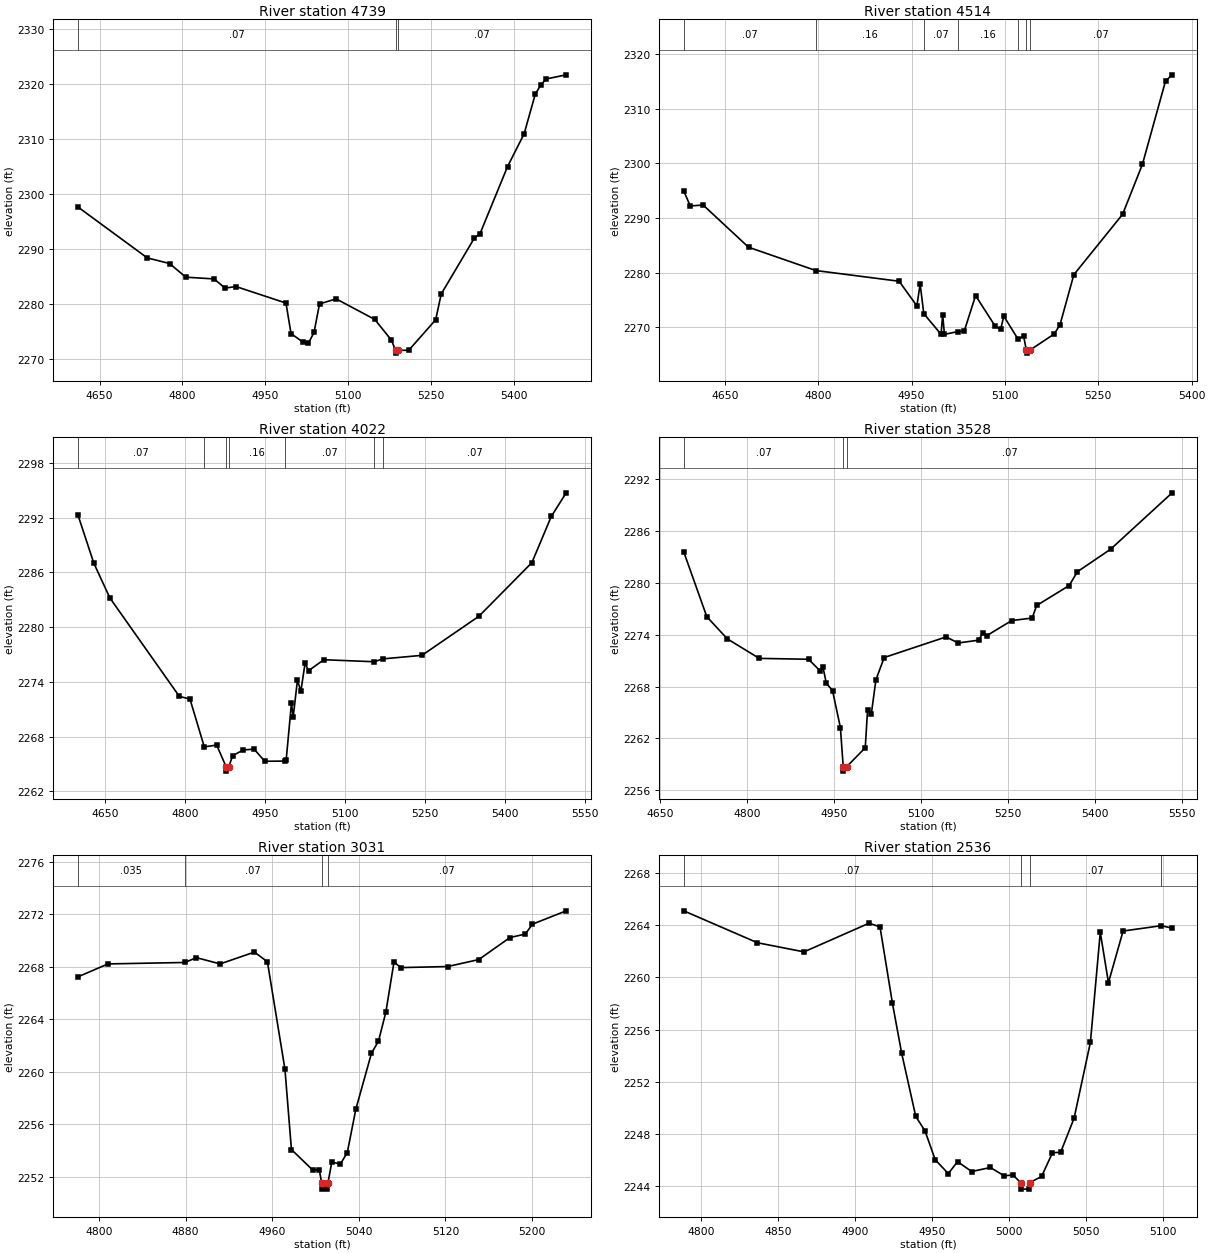
Type RM Length L Ch R = 1,4739,225,225,225
BEGIN DESCRIPTION:
Rough Creek Trib1 4016
END DESCRIPTION:
XS GIS Cut Line= 3
      1357070.03      6861251.04      1357456.96      6861293.89
      1357950.98      6861315.75
#Sta/Elev= 30
  4610.7 2297.66  4736.4 2288.37  4776.7 2287.35  4806.0 2284.86  4857.2 2284.54
  4877.3 2282.86  4896.7 2283.16  4987.4 2280.14  4996.5 2274.59  5018.1 2273.02
  5028.1 2272.85  5038.1 2274.79  5048.1 2279.98  5078.1 2280.91  5148.2 2277.15
  5178.2 2273.39  5185.7 2271.52  5186.0 2271.02  5190.8 2271.52  5209.7 2271.55
  5258.3 2277.10  5268.3 2281.79  5328.4 2292.00  5338.4 2292.75  5388.4 2305.02
  5418.4 2310.99  5438.5 2318.20  5448.5 2319.88  5458.5 2320.98  5494.5 2321.73
#Mann=3,-1,0
  4610.7    0.07       0  5185.7    0.07       0  5190.8    0.07       0
Bank Sta=5185.7,5190.8
Exp/Cntr=0.3,0.1

Type RM Length L Ch R = 1,4514,492,492,492
BEGIN DESCRIPTION:
Rough Creek Trib1 8.0
END DESCRIPTION:
XS GIS Cut Line= 3
      1357104.98      6861387.99      1357504.85      6861503.06
      1357855.03      6861387.99
#Sta/Elev= 30
  4583.9 2294.97  4594.3 2292.22  4615.1 2292.38  4688.0 2284.67  4796.1 2280.41
  4930.0 2278.45  4958.5 2273.94  4963.7 2277.95  4969.6 2272.53  4997.4 2268.74
  4999.9 2272.34  5002.8 2268.74  5024.8 2269.26  5034.6 2269.33  5052.8 2275.83
  5084.4 2270.22  5093.0 2269.63  5098.2 2272.06  5121.2 2267.84  5130.0 2268.45
  5134.4 2265.81  5134.8 2265.31  5139.6 2265.81  5179.1 2268.81  5188.4 2270.47
  5210.7 2279.65  5289.1 2290.70  5320.9 2299.83  5358.0 2315.05  5368.6 2316.19
#Mann=7,-1,0
  4583.9    0.07       0  4796.1    0.16       0  4969.6    0.07       0
  5024.8    0.16       0  5121.2    0.07       0  5134.4    0.07       0
  5139.6    0.07       0
Bank Sta=5134.4,5139.6
Exp/Cntr=0.3,0.1

Type RM Length L Ch R = 1,4022,494,494,494
BEGIN DESCRIPTION:
Rough Creek Trib1 7.0
END DESCRIPTION:
XS GIS Cut Line= 3
      1357104.98      6861938.00      1357505.00      6861963.00
      1357905.01      6861637.99
#Sta/Elev= 30
  4599.2 2292.32  4629.3 2286.99  4659.3 2283.20  4789.6 2272.42  4809.6 2272.12
  4836.4 2266.89  4859.7 2267.08  4877.2 2264.73  4877.6 2264.23  4882.4 2264.73
  4889.8 2265.93  4909.8 2266.55  4929.9 2266.64  4949.9 2265.31  4988.0 2265.33
  4990.0 2265.41  5000.0 2271.68  5003.2 2270.16  5011.2 2274.19  5017.6 2272.97
  5025.5 2276.04  5032.0 2275.23  5060.7 2276.43  5155.3 2276.21  5171.0 2276.52
  5244.8 2276.91  5351.6 2281.19  5451.0 2287.06  5487.4 2292.12  5515.4 2294.71
#Mann=7,-1,0
  4599.2    0.07       0  4836.4    0.16       0  4877.2    0.07       0
  4882.4    0.16       0  4988.0    0.07       0  5155.3    0.16       0
  5171.0    0.07       0
Bank Sta=4877.2,4882.4
Exp/Cntr=0.3,0.1

Type RM Length L Ch R = 1,3528,497,497,497
BEGIN DESCRIPTION:
Rough Creek Trib1 6.0
END DESCRIPTION:
XS GIS Cut Line= 3
      1357605.01      6862487.98      1357714.81      6862198.51
      1358054.97      6861788.04
#Sta/Elev= 30
  4690.4 2283.55  4730.2 2276.06  4765.7 2273.50  4820.7 2271.25  4905.7 2271.15
  4925.2 2269.84  4930.5 2270.28  4936.4 2268.38  4947.1 2267.54  4960.7 2263.26
  4965.6 2258.73  4966.0 2258.23  4971.4 2258.73  5003.6 2260.93  5007.6 2265.31
  5014.1 2264.85  5022.0 2268.78  5036.3 2271.35  5143.1 2273.73  5163.9 2273.03
  5199.1 2273.35  5206.9 2274.22  5213.4 2273.88  5256.4 2275.62  5291.6 2275.91
  5299.4 2277.36  5355.4 2279.66  5369.7 2281.26  5427.0 2283.86  5533.1 2290.37
#Mann=3,-1,0
  4690.4    0.07       0  4965.6    0.07       0  4971.4    0.07       0
Bank Sta=4965.6,4971.4
Exp/Cntr=0.3,0.1

Type RM Length L Ch R = 1,3031,495,495,495
BEGIN DESCRIPTION:
Rough Creek Trib1 5.0
END DESCRIPTION:
XS GIS Cut Line= 4
      1357901.61      6862544.08      1358005.00      6862488.00
      1358094.55      6862439.43      1358274.22      6862293.28
#Sta/Elev= 30
  4780.5 2267.23  4808.3 2268.22  4879.4 2268.33  4890.0 2268.70  4911.9 2268.22
  4943.6 2269.12  4955.6 2268.39  4971.8 2260.19  4977.8 2254.06  4997.4 2252.50
  5003.5 2252.50  5005.7 2251.54  5006.2 2251.04  5011.1 2251.04  5011.6 2251.54
  5015.1 2253.11  5023.0 2252.95  5029.4 2253.83  5037.3 2257.14  5051.7 2261.40
  5058.2 2262.33  5065.0 2264.53  5072.5 2268.35  5079.0 2267.94  5122.1 2268.02
  5150.8 2268.55  5179.6 2270.23  5193.9 2270.50  5200.4 2271.25  5231.6 2272.27
#Mann=4,-1,0
  4780.5   0.035       0  4879.4    0.07       0  5005.7    0.07       0
  5011.6    0.07       0
Bank Sta=5005.7,5011.6
Exp/Cntr=0.3,0.1

Type RM Length L Ch R = 1,2536,499,499,499
BEGIN DESCRIPTION:
Rough Creek Trib1 4.0
END DESCRIPTION:
XS GIS Cut Line= 4
      1358178.22      6862887.90      1358255.00      6862838.00
      1358355.22      6862772.86      1358455.01      6862738.00
#Sta/Elev= 30
  4788.9 2265.11  4836.7 2262.66  4866.9 2261.96  4909.1 2264.16  4916.2 2263.88
  4924.3 2258.00  4930.2 2254.21  4939.4 2249.33  4945.4 2248.22  4952.0 2246.01
  4960.5 2244.94  4966.5 2245.86  4975.7 2245.10  4987.8 2245.41  4996.8 2244.77
  5002.5 2244.84  5007.4 2244.25  5007.9 2243.75  5012.9 2243.75  5013.4 2244.25
  5021.0 2244.72  5028.1 2246.54  5033.4 2246.58  5042.1 2249.19  5052.7 2255.02
  5059.1 2263.46  5064.4 2259.60  5073.9 2263.56  5098.7 2263.97  5105.7 2263.78
#Mann=4,-1,0
  4788.9    0.07       0  5007.4    0.07       0  5013.4    0.07       0
  5098.7    0.16       0
Bank Sta=5007.4,5013.4
Exp/Cntr=0.3,0.1