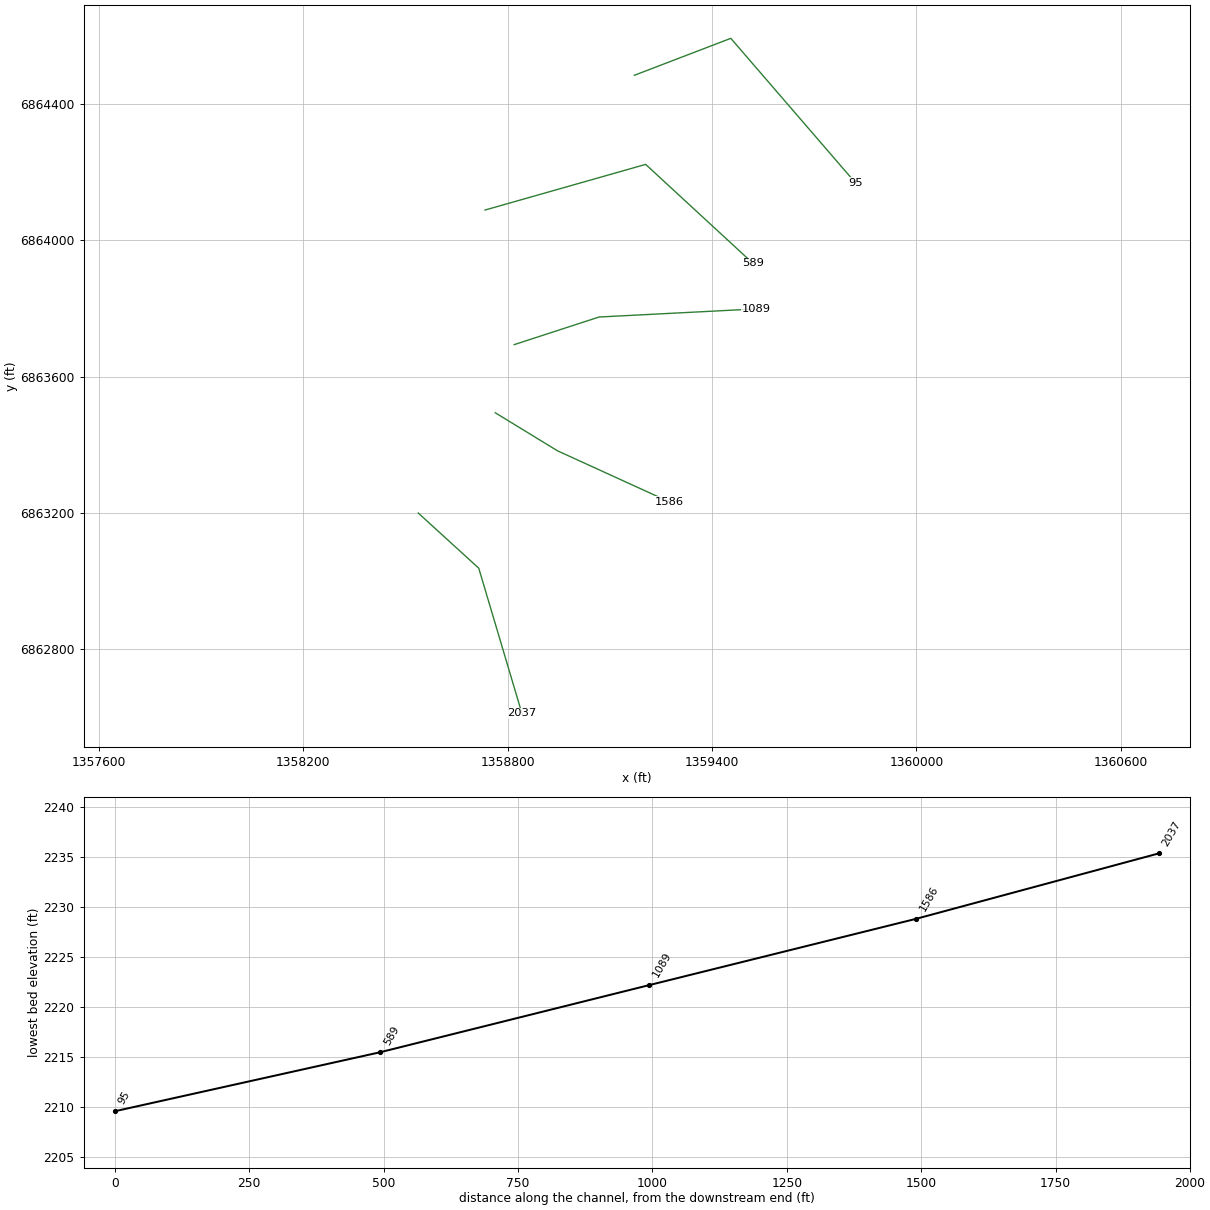
HEC-RAS study Rough Creek Trib1.prj: Rough Creek Trib1 Base Level Engineering

--- Rough Creek Trib1.g01 (geometry) --- (continued)

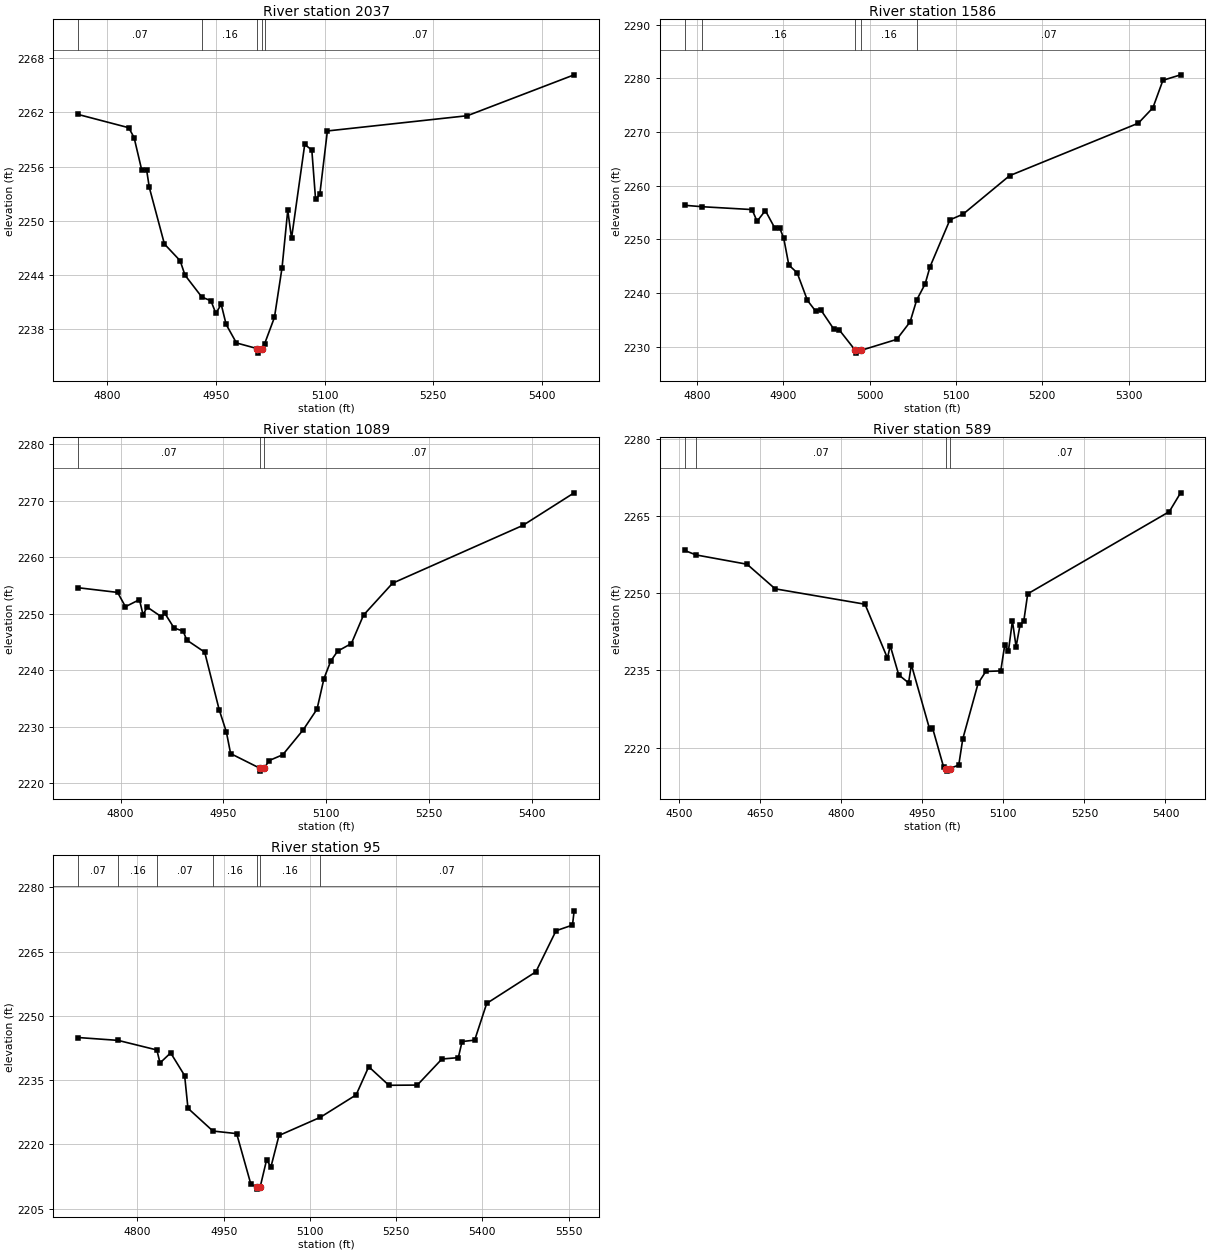
Type RM Length L Ch R = 1,2037,451,451,451
BEGIN DESCRIPTION:
Rough Creek Trib1 3.0
END DESCRIPTION:
XS GIS Cut Line= 4
      1358537.61      6863199.44      1358605.00      6863138.00
      1358715.19      6863037.55      1358841.90      6862611.39
#Sta/Elev= 30
  4759.7 2261.78  4829.6 2260.31  4837.0 2259.22  4847.5 2255.64  4854.3 2255.64
  4858.0 2253.70  4878.9 2247.42  4900.6 2245.57  4907.3 2243.97  4930.6 2241.54
  4943.1 2241.13  4949.9 2239.74  4957.3 2240.74  4964.1 2238.51  4978.3 2236.46
  5007.0 2235.83  5007.5 2235.33  5013.0 2235.83  5017.3 2236.38  5030.8 2239.29
  5041.3 2244.80  5049.2 2251.17  5054.4 2248.05  5072.6 2258.45  5082.4 2257.84
  5087.6 2252.37  5093.4 2252.91  5103.9 2259.95  5297.2 2261.64  5444.6 2266.17
#Mann=5,-1,0
  4759.7    0.07       0  4930.6    0.16       0  5007.0    0.07       0
  5013.0    0.16       0  5017.3    0.07       0
Bank Sta=5007,5013
Exp/Cntr=0.3,0.1

Type RM Length L Ch R = 1,1586,497,497,497
BEGIN DESCRIPTION:
Rough Creek Trib1 2.0
END DESCRIPTION:
XS GIS Cut Line= 4
      1358763.51      6863493.89      1358855.00      6863438.00
      1358946.56      6863382.07      1359274.23      6863232.50
#Sta/Elev= 30
  4785.5 2256.34  4806.2 2256.07  4863.7 2255.54  4869.5 2253.36  4879.1 2255.35
  4889.8 2252.17  4895.6 2252.17  4900.4 2250.20  4906.3 2245.20  4915.9 2243.77
  4927.9 2238.60  4937.2 2236.65  4943.1 2236.91  4958.5 2233.24  4964.4 2233.18
  4983.4 2229.29  4983.9 2228.79  4989.6 2229.29  5031.3 2231.35  5046.8 2234.61
  5054.4 2238.68  5064.2 2241.68  5069.9 2244.89  5092.9 2253.62  5108.2 2254.69
  5162.0 2261.85  5311.2 2271.64  5328.1 2274.51  5339.7 2279.63  5360.2 2280.65
#Mann=5,-1,0
  4785.5    0.07       0  4806.2    0.16       0  4983.4    0.07       0
  4989.6    0.16       0  5054.4    0.07       0
Bank Sta=4983.4,4989.6
Exp/Cntr=0.3,0.1

Type RM Length L Ch R = 1,1089,500,500,500
BEGIN DESCRIPTION:
Rough Creek Trib1 1.0
END DESCRIPTION:
XS GIS Cut Line= 4
      1358819.34      6863693.85      1358955.00      6863738.00
      1359068.48      6863774.93      1359529.57      6863798.65
#Sta/Elev= 30
  4738.0 2254.62  4795.6 2253.79  4807.1 2251.26  4827.5 2252.51  4832.8 2249.80
  4838.6 2251.21  4859.4 2249.49  4864.7 2250.06  4878.0 2247.49  4891.2 2246.94
  4896.6 2245.35  4922.7 2243.21  4943.8 2233.04  4954.3 2229.09  4960.5 2225.26
  5003.4 2222.65  5003.9 2222.15  5009.7 2222.65  5016.5 2224.01  5036.6 2225.05
  5066.6 2229.49  5086.6 2233.13  5096.7 2238.54  5106.7 2241.66  5116.7 2243.39
  5136.7 2244.74  5154.4 2249.77  5196.8 2255.42  5387.0 2265.66  5461.7 2271.42
#Mann=3,-1,0
  4738.0    0.07       0  5003.4    0.07       0  5009.7    0.07       0
Bank Sta=5003.4,5009.7
Exp/Cntr=0.3,0.1

Type RM Length L Ch R = 1,589,494,494,494
BEGIN DESCRIPTION:
Sweetwater Creek Trib 7 15.0
END DESCRIPTION:
XS GIS Cut Line= 3
      1358733.71      6864088.95      1359205.13      6864222.94
      1359519.73      6863932.75
#Sta/Elev= 30
  4509.9 2258.34  4531.1 2257.46  4625.6 2255.65  4677.6 2250.87  4843.9 2247.88
  4885.4 2237.41  4890.6 2239.81  4906.3 2234.15  4924.5 2232.59  4929.7 2236.12
  4963.6 2223.55  4968.7 2223.90  4989.5 2216.17  4994.2 2215.94  4994.7 2215.44
  5000.5 2215.94  5017.4 2216.62  5024.8 2221.69  5053.2 2232.49  5067.4 2234.81
  5095.1 2234.92  5102.5 2239.96  5109.3 2238.80  5116.7 2244.63  5123.5 2239.62
  5130.9 2243.91  5137.7 2244.58  5145.0 2249.90  5407.0 2265.87  5428.0 2269.53
#Mann=4,-1,0
  4509.9   0.035       0  4531.1    0.07       0  4994.2    0.07       0
  5000.5    0.07       0
Bank Sta=4994.2,5000.5
Exp/Cntr=0.3,0.1

Type RM Length L Ch R = 1,95,0,0,0
BEGIN DESCRIPTION:
Rough Creek Trib1 4355
END DESCRIPTION:
XS GIS Cut Line= 3
      1359171.94      6864484.51      1359455.08      6864592.97
      1359820.61      6864169.25
#Sta/Elev= 30
  4696.8 2244.95  4766.4 2244.28  4833.8 2242.04  4839.3 2239.01  4857.8 2241.36
  4882.1 2236.06  4887.9 2228.42  4931.3 2223.10  4972.6 2222.50  4997.3 2210.68
  5007.2 2210.03  5007.7 2209.53  5013.5 2210.03  5024.6 2216.33  5032.3 2214.76
  5046.2 2222.06  5118.1 2226.31  5180.4 2231.55  5202.3 2238.13  5237.4 2233.79
  5286.8 2233.84  5329.6 2239.93  5358.1 2240.25  5364.7 2244.01  5386.6 2244.34
  5407.5 2252.92  5493.0 2260.29  5528.1 2269.90  5556.7 2271.22  5559.6 2274.55
#Mann=7,-1,0
  4696.8    0.07       0  4766.4    0.16       0  4833.8    0.07       0
  4931.3    0.16       0  5007.2    0.07       0  5013.5    0.16       0
  5118.1    0.07       0
Bank Sta=5007.2,5013.5
Exp/Cntr=0.3,0.1

Chan Stop Cuts=-1