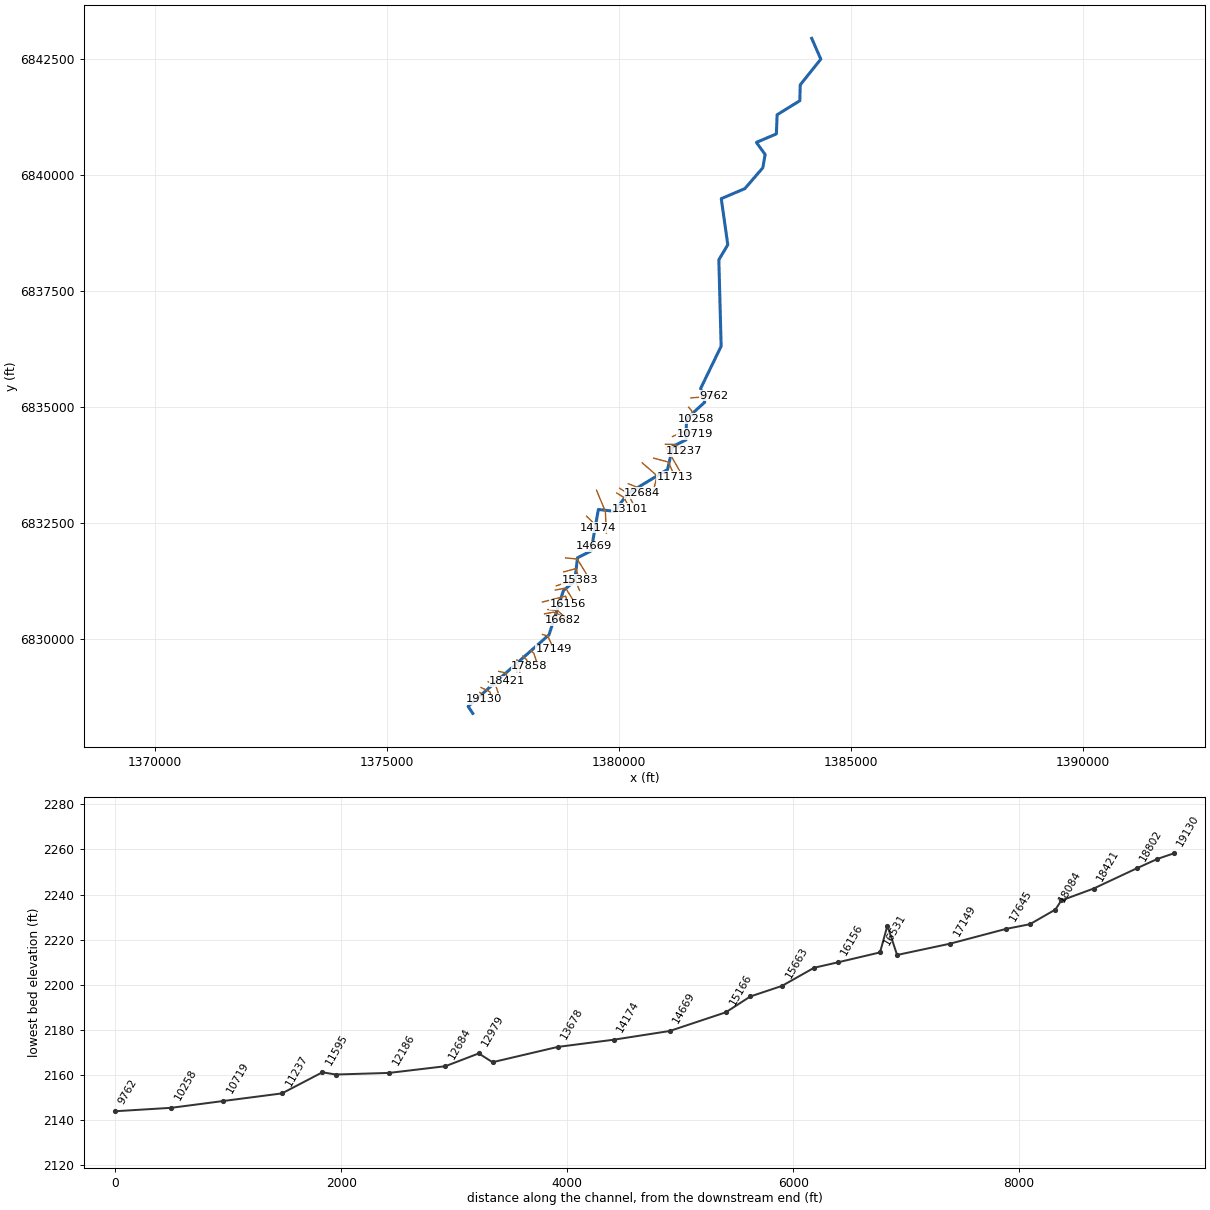
--- Salt Branch.prj (project) ---

Proj Title=Salt Branch Base Level Engineering
Current Plan=p01
Default Exp/Contr=0.3,0.1
English Units
Geom File=g01
Flow File=f01
Plan File=p01
Y Axis Title=Elevation
X Axis Title(PF)=Main Channel Distance
X Axis Title(XS)=Station
BEGIN DESCRIPTION:
Salt Branch
END DESCRIPTION:
DSS File=dss
DSS Export Rating Curves= 0
DSS Export Rating Curve Sorted= 0
DSS Export Volume Flow Curves= 0
DXF OffsetX= 0
DXF OffsetY= 0
DXF ScaleX= 1
DXF ScaleY= 10

--- Salt Branch.p01 (plan) ---

Plan Title=Multiple Run
Program Version=4.10
Geom File=g01
Subcritical Flow
K Sum by GR= 0
Std Step Tol= 0.01
Critical Tol= 0.01
Num of Std Step Trials= 20
Max Error Tol= 0.3
Flow Tol Ratio= 0.001
Split Flow NTrial= 30
Split Flow Tol= 0.02
Split Flow Ratio= 0.02
Log Output Level= 0
Friction Slope Method= 1
Unsteady Friction Slope Method= 2
Unsteady Bridges Friction Slope Method= 1
Parabolic Critical Depth
Global Vel Dist= 1 , 1 , 1
Global Log Level= 0
CheckData=True
Encroach Param=-1 ,0,0, 0
BEGIN DESCRIPTION:
Multiple Run
END DESCRIPTION:
Computation Interval=1HOUR
Output Interval=1HOUR
Run HTab= 0
Run UNet= 0
Run PostProcess= 0
Run WQNet= 0
UNET Theta= 1
UNET Theta Warmup= 1
UNET ZTol= 0.02
UNET ZSATol= 0.05
UNET MxIter= 20
UNET MaxInSteps= 0
UNET DtIC= 0
UNET DtMin= 0
UNET MaxCRTS= 20
UNET WFStab= 2
UNET SFStab= 1
UNET WFX= 1
UNET SFX= 1
UNET DSS MLevel= 4
UNET DZMax Abort= 100
UNET Convert EG Bridges= 0
UNET Use Existing IB Tables=-1
UNET Froude Reduction=False
UNET Froude Limit= 1
UNET Froude Power= 10
UNET Time Slicing=0,0, 5
UNET Junction Losses=0
Instantaneous Interval=1HOUR
DSS File=dss
Write IC File= 0
Write IC File at Sim End=0
Echo Input=False
Echo Parameters=False
Echo Output=False
Write Detailed= 0
WQ AD Non Conservative
WQ ULTIMATE=-1
WQ Max Comp Step=1HOUR
WQ Output Interval=15MIN
WQ Output Selected Increments= 0
WQ Output face flow=0
WQ Output face velocity=0
WQ Output face area=0
WQ Output face dispersion=0
WQ Output cell volume=0
WQ Output cell surface area=0
WQ Output cell continuity=0
WQ Output cumulative cell continuity=0
WQ Output face conc=0
WQ Output face dconc_dx=0
WQ Output face courant=0
WQ Output face peclet=0
WQ Output face adv mass=0
WQ Output face disp mass=0
WQ Output cell mass=0
WQ Output cell source sink temp=0
WQ Output cell source sink nsm=0
WQ Output MaxMinRange=-1
WQ Daily Max Min Mean=-1
WQ Daily Range=0
WQ Daily Time=0
WQ Create Restart=0
WQ Fixed Restart=0
WQ System Summary=0
WQ Use Fixed Temperature=0
Sorting and Armoring Iterations= 10
XS Update Threshold= 0.02
Hydraulics Update Threshold= 0.02
Energy Slope Method= 1
Volume Change Method= 0
XS Weighting Method= 0
Number of US Weighted Cross Sections= 1
Number of DS Weighted Cross Sections= 1
Upstream XS Weight=0.25
Main XS Weight=0.5
Downstream XS Weight=0.25
Number of DS XS's Weighted with US Boundary= 1
Upstream Boundary Weight= 1
Weight of XSs Associated with US Boundary= 0
Number of US XS's Weighted with DS Boundary= 1
Downstream Boundary Weight= 0.5
Weight of XSs Associated with DS Boundary= 0.5
Sediment Output Level= 4
Mass or Volume Output= 0
Output Increment Type= 1
Profile and TS Output Increment= 10
XS Output Flag= 0
XS Output Increment= 10
Disregard all LS=0
Disregard all Conn=0
Disregard all Breaches=0
Disregard all Pumps=0

--- Salt Branch.f01 (steady flow) ---

Flow Title=Multiple
Number of Profiles=7
Profile Names=10-year,25-year,50-year,1pct_min,100-year,1pct_plu,500-year
River Rch & RM= Salt Branch,Reach-1,19130
     207     291     362     225     449     895     696
River Rch & RM= Salt Branch,Reach-1,13101
     305     438     552     347     691    1380    1097
River Rch & RM= Salt Branch,Reach-1,9762
     311     446     560     350     698    1393    1101
River Rch & RM= Salt Branch,Reach-1,6942
     432     629     798     503    1005    2004    1613
River Rch & RM= Salt Branch,Reach-1,4584
     439     639     810     510    1018    2032    1632
River Rch & RM= Salt Branch,Reach-1,2188
     586     865    1109     705    1407    2807    2296
River Rch & RM= Salt Branch,Reach-1,1735
     576     847    1083     687    1370    2734    2226
Boundary for River Rch & Prof#=Salt Branch,Reach-1,1
Up Type=0
Dn Type=3
Dn Slope=0.005
Boundary for River Rch & Prof#=Salt Branch,Reach-1,2
Up Type=0
Dn Type=3
Dn Slope=0.005
Boundary for River Rch & Prof#=Salt Branch,Reach-1,3
Up Type=0
Dn Type=3
Dn Slope=0.005
Boundary for River Rch & Prof#=Salt Branch,Reach-1,4
Up Type=0
Dn Type=3
Dn Slope=0.005
Boundary for River Rch & Prof#=Salt Branch,Reach-1,5
Up Type=0
Dn Type=3
Dn Slope=0.005
Boundary for River Rch & Prof#=Salt Branch,Reach-1,6
Up Type=0
Dn Type=3
Dn Slope=0.005
Boundary for River Rch & Prof#=Salt Branch,Reach-1,7
Up Type=0
Dn Type=3
Dn Slope=0.005

--- Salt Branch.g01 (geometry) ---

Geom Title=Existing Conditions
Program Version=4.10

River Reach=Salt Branch     ,Reach-1
Reach XY= 30
        1376855.        6828388.        1376755.        6828538.
      1378496.86      6830081.94      1378808.12      6831036.38
      1379051.48      6831239.46      1379110.34      6831740.74
      1379401.47      6831889.45      1379560.11      6832783.04
      1379907.48       6832743.4      1380195.29      6833127.25
      1381050.19      6833643.62      1381162.62       6834144.5
      1381445.94      6834280.99      1381458.75      6834736.45
      1381851.94      6835095.62      1381763.05      6835391.29
      1382204.46      6836301.86      1382154.89      6838165.32
      1382347.47      6838487.99      1382207.17      6839482.56
       1382714.8      6839698.48        1383101.      6840146.33
      1383152.83      6840432.56       1382964.1      6840694.75
      1383394.25      6840878.29       1383410.3      6841290.54
      1383899.42      6841593.58      1383908.33      6841936.31
      1384351.46      6842489.47        1384155.        6842938.

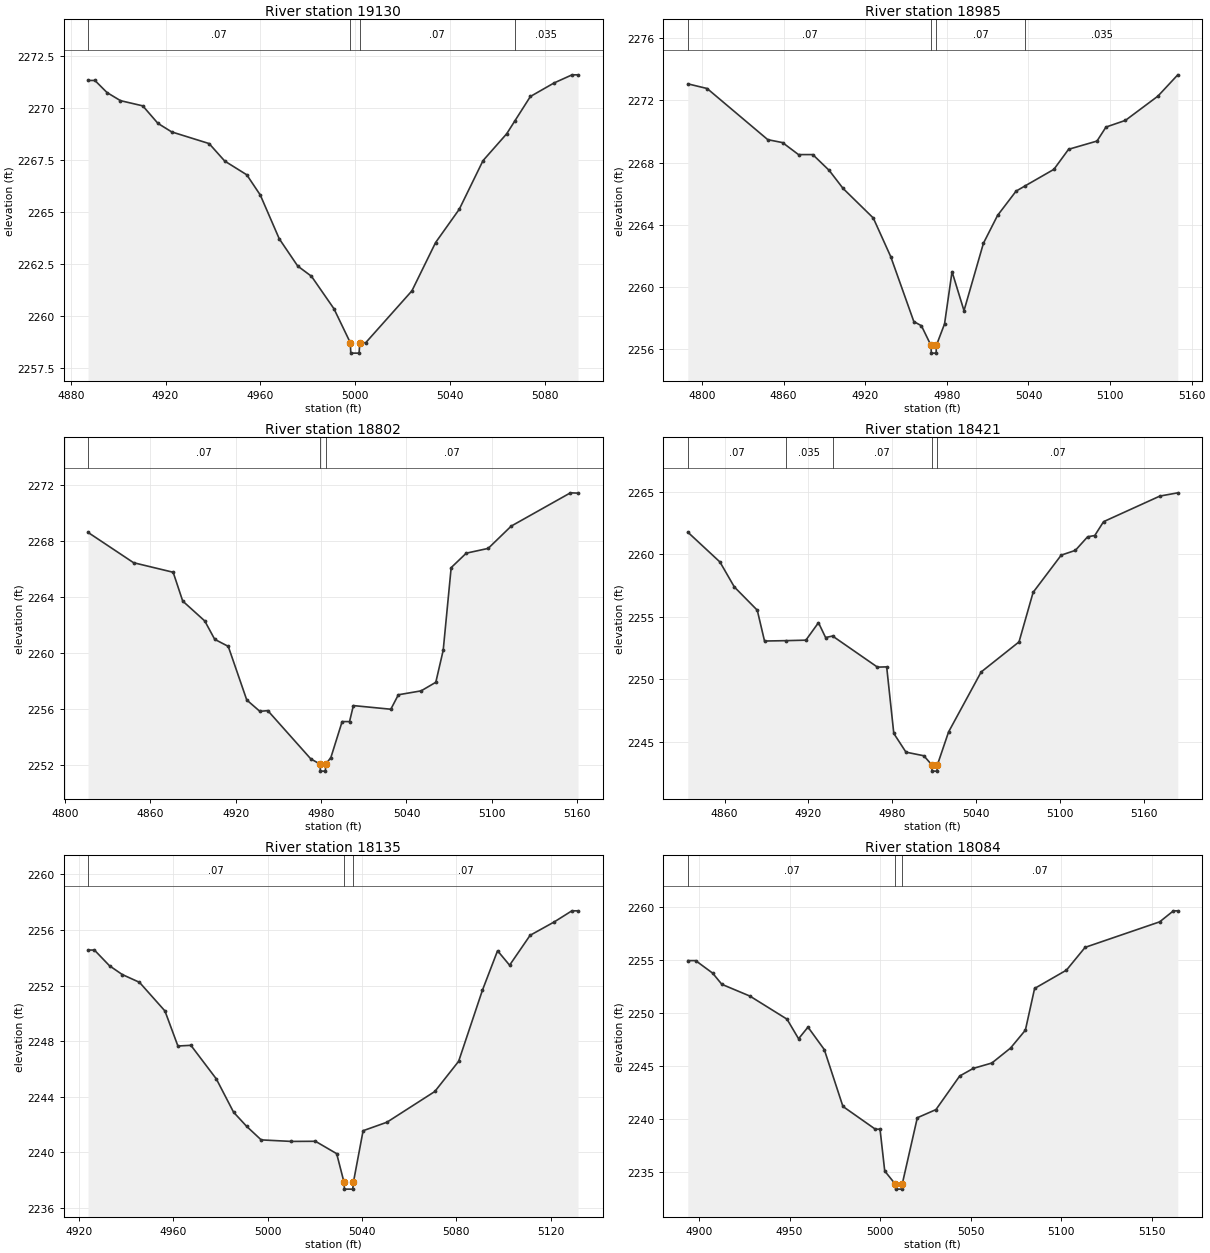
Type RM Length L Ch R = 1 ,19130   ,145,145,145
BEGIN DESCRIPTION:
Salt Branch 38.0
END DESCRIPTION:
XS GIS Cut Line= 3
      1377004.96      6828838.02      1377102.76      6828782.03
        1377105.      6828687.95
#Sta/Elev= 30
  4887.3 2271.31  4890.2 2271.31  4895.3 2270.73    4901 2270.34  4910.4 2270.09
  4916.8 2269.25  4922.6 2268.84  4938.4 2268.28    4945 2267.44  4954.3 2266.78
    4960 2265.81    4968 2263.71  4975.8  2262.4  4981.6 2261.91  4991.1 2260.35
    4998 2258.72  4998.2 2258.22  5001.7 2258.22    5002 2258.72  5004.5 2258.72
    5024 2261.21    5034 2263.53    5044 2265.13    5054 2267.46    5064 2268.75
  5067.4 2269.36    5074 2270.54    5084 2271.19  5091.6 2271.58  5094.1 2271.58
#Mann= 4 ,-1 , 0
  4887.3     .07       0    4998     .07       0    5002     .07       0
  5067.4    .035       0
Bank Sta=4998,5002
XS Rating Curve= 0 ,0
Exp/Cntr=0.3,0.1

Type RM Length L Ch R = 1 ,18985   ,183,183,183
BEGIN DESCRIPTION:
Salt Branch 4428
END DESCRIPTION:
XS GIS Cut Line= 3
      1377032.25      6828946.32       1377221.7      6828854.58
      1377264.82      6828711.12
#Sta/Elev= 30
  4789.5 2273.07  4803.7 2272.77  4848.3 2269.48  4859.2 2269.29  4870.9 2268.52
  4881.4 2268.52  4893.5  2267.5  4903.7 2266.34  4925.9 2264.44  4938.7 2261.96
  4955.7 2257.78  4961.3 2257.51  4968.3 2256.25  4968.6 2255.75  4972.1 2255.75
  4972.3 2256.25  4978.3 2257.63  4983.8 2260.99  4992.6 2258.48  5006.9 2262.82
  5017.3 2264.61  5030.9 2266.17  5037.8 2266.52  5058.7 2267.57  5069.5 2268.86
  5090.4 2269.39    5097 2270.29  5111.3 2270.72  5135.2 2272.28  5149.8 2273.65
#Mann= 4 ,-1 , 0
  4789.5     .07       0  4968.3     .07       0  4972.3     .07       0
  5037.8    .035       0
Bank Sta=4968.3,4972.3
XS Rating Curve= 0 ,0
Exp/Cntr=0.3,0.1

Type RM Length L Ch R = 1 ,18802   ,381,381,381
BEGIN DESCRIPTION:
Salt Branch 4427
END DESCRIPTION:
XS GIS Cut Line= 3
      1377185.95      6829069.99      1377349.17       6828985.7
      1377400.17      6828833.52
#Sta/Elev= 30
  4816.3 2268.59  4848.3 2266.43  4876.1 2265.75  4882.8  2263.7  4898.3 2262.28
  4905.3 2260.97  4914.8 2260.47  4927.8 2256.65    4937 2255.84  4942.6 2255.89
  4972.8 2252.45  4979.3 2252.08  4979.5 2251.58    4983 2251.58  4983.3 2252.08
  4986.9 2252.55  4994.8 2255.11    5000 2255.11  5002.7 2256.25    5029 2255.99
  5034.3 2257.02  5050.3  2257.3  5060.6 2257.91  5065.8 2260.19  5071.4 2266.08
    5082 2267.11  5097.4 2267.45  5113.6 2269.04  5155.2 2271.41  5160.5 2271.39
#Mann= 3 ,-1 , 0
  4816.3     .07       0  4979.3     .07       0  4983.3     .07       0
Bank Sta=4979.3,4983.3
XS Rating Curve= 0 ,0
Exp/Cntr=0.3,0.1

Type RM Length L Ch R = 1 ,18421   ,286.02,286.02,286.02
BEGIN DESCRIPTION:
Salt Branch 4429
END DESCRIPTION:
XS GIS Cut Line= 3
      1377412.52      6829293.95      1377574.93      6829258.17
      1377597.39      6829075.25
#Sta/Elev= 30
  4833.7 2261.78  4856.7 2259.39    4867 2257.39  4883.4 2255.53  4888.6 2253.06
  4903.8 2253.09  4918.2 2253.13  4927.2 2254.53  4932.3 2253.34  4937.3 2253.46
  4969.4 2250.97    4976 2250.99  4981.1 2245.66  4989.8 2244.16  5002.6 2243.87
  5008.3 2243.14  5008.5 2242.64    5012 2242.64  5012.3 2243.14  5020.3 2245.78
  5043.6 2250.58  5070.7 2252.99  5080.8 2256.96  5100.9 2259.94    5111 2260.32
  5119.8 2261.41  5124.9 2261.51  5131.2 2262.62  5171.5 2264.67  5184.3 2264.93
#Mann= 5 ,-1 , 0
  4833.7     .07       0  4903.8    .035       0  4937.3     .07       0
  5008.3     .07       0  5012.3     .07       0
Bank Sta=5008.3,5012.3
XS Rating Curve= 0 ,0
Exp/Cntr=0.3,0.1

Type RM Length L Ch R = 1 ,18135   ,51,51,51
BEGIN DESCRIPTION:
Salt Branch 36.0
END DESCRIPTION:
XS GIS Cut Line= 3
        1377755.        6829488.      1377784.91      6829418.03
        1377805.      6829287.97
#Sta/Elev= 30
  4923.9 2254.55  4926.6 2254.55    4933 2253.42  4938.4 2252.79  4945.7 2252.23
  4956.5 2250.17    4962 2247.65  4967.5  2247.7  4978.3 2245.28  4985.6 2242.89
  4991.1 2241.88  4997.3  2240.9  5010.1 2240.79  5020.3  2240.8  5029.3 2239.91
  5032.4 2237.86  5032.6 2237.36  5036.1 2237.36  5036.4 2237.86  5040.5 2241.56
  5050.6 2242.17  5070.9 2244.38    5081 2246.55  5091.1 2251.67  5097.5  2254.5
  5102.6 2253.46  5111.3 2255.61  5121.5 2256.57    5129 2257.37  5131.6 2257.37
#Mann= 3 ,-1 , 0
  4923.9     .07       0  5032.4     .07       0  5036.4     .07       0
Bank Sta=5032.4,5036.4
XS Rating Curve= 0 ,0
Exp/Cntr=0.3,0.1

Type RM Length L Ch R = 1 ,18084   ,226,226,226
BEGIN DESCRIPTION:
Salt Branch 4425
END DESCRIPTION:
XS GIS Cut Line= 3
      1377805.72      6829541.39      1377829.99        6829438.
      1377869.53      6829278.33
#Sta/Elev= 30
  4893.8 2254.95  4898.1 2254.95  4907.5 2253.77  4912.6 2252.71  4928.1  2251.6
  4948.6 2249.42    4955 2247.57  4960.2 2248.67  4969.2 2246.55  4979.5 2241.18
  4997.4 2239.03    5000 2239.03  5002.6 2235.08  5008.3 2233.87  5008.6 2233.37
  5012.1 2233.37  5012.3 2233.87  5020.6 2240.11  5030.9 2240.88    5044 2244.05
  5051.5 2244.77  5061.8 2245.28  5072.1 2246.69  5080.3 2248.38  5085.4 2252.32
    5103 2254.05  5113.3  2256.2  5154.5 2258.61  5162.1 2259.65  5164.5 2259.65
#Mann= 3 ,-1 , 0
  4893.8     .07       0  5008.3     .07       0  5012.3     .07       0
Bank Sta=5008.3,5012.3
XS Rating Curve= 0 ,0
Exp/Cntr=0.3,0.1

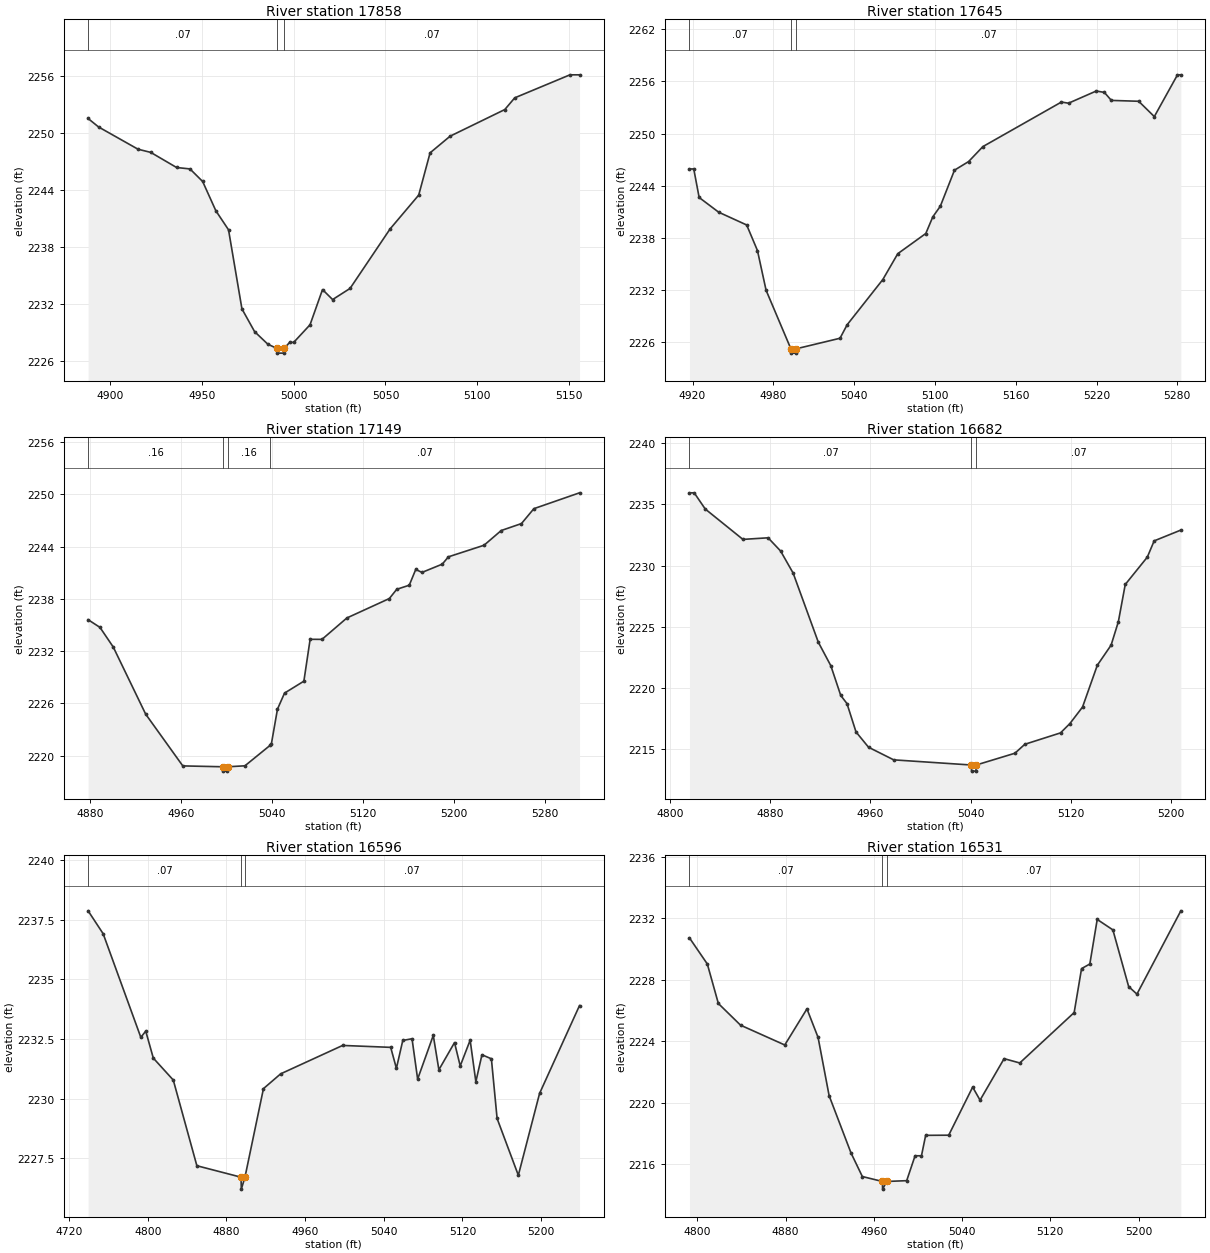
Type RM Length L Ch R = 1 ,17858   ,213,213,213
BEGIN DESCRIPTION:
Salt Branch 4424
END DESCRIPTION:
XS GIS Cut Line= 3
      1377932.05      6829623.36      1378013.18      6829546.14
      1378075.25      6829403.35
#Sta/Elev= 30
    4888 2251.52  4893.7 2250.63  4915.2 2248.29  4922.1 2247.96  4936.2 2246.37
  4943.5 2246.22  4950.4  2244.9  4957.6 2241.82  4964.5 2239.82  4971.8 2231.51
  4978.7 2229.12  4985.9  2227.8  4990.8 2227.36  4991.1 2226.86  4994.6 2226.86
  4994.8 2227.36  4997.8 2227.99    5000 2227.99  5008.9 2229.84  5015.7 2233.54
  5021.2 2232.49  5030.7 2233.66  5052.5 2239.91  5068.1 2243.47  5074.3 2247.91
  5085.2 2249.66    5115 2252.46  5120.4 2253.69  5150.5 2256.11  5155.7 2256.11
#Mann= 3 ,-1 , 0
    4888     .07       0  4990.8     .07       0  4994.8     .07       0
Bank Sta=4990.8,4994.8
XS Rating Curve= 0 ,0
Exp/Cntr=0.3,0.1

Type RM Length L Ch R = 1 ,17645   ,496,496,496
BEGIN DESCRIPTION:
Salt Branch 35.0
END DESCRIPTION:
XS GIS Cut Line= 3
      1378104.98      6829738.01      1378169.42      6829686.82
      1378257.48      6829418.29
#Sta/Elev= 30
  4917.7 2245.93  4920.9 2245.93  4924.9 2242.65  4939.4 2240.96  4960.2 2239.49
  4968.2 2236.55  4974.6 2231.99    4993 2225.26  4993.3 2224.76  4996.8 2224.76
    4997 2225.26  5029.5 2226.47  5034.8 2228.02  5061.3 2233.22  5072.4 2236.19
  5093.2 2238.51  5098.4 2240.42    5104 2241.65  5114.5 2245.79    5125 2246.78
  5135.6  2248.5  5193.9 2253.62  5199.2 2253.49  5219.8 2254.89  5225.8 2254.73
    5231 2253.81  5251.3 2253.71  5262.9 2251.95  5280.1 2256.75  5282.6 2256.75
#Mann= 3 ,-1 , 0
  4917.7     .07       0    4993     .07       0    4997     .07       0
Bank Sta=4993,4997
XS Rating Curve= 0 ,0
Exp/Cntr=0.3,0.1

Type RM Length L Ch R = 1 ,17149   ,467,467,467
BEGIN DESCRIPTION:
Salt Branch 34.0
END DESCRIPTION:
XS GIS Cut Line= 3
      1378355.04      6830087.99      1378472.04      6830054.51
      1378598.58      6829771.41
#Sta/Elev= 30
  4878.3  2235.6  4888.7 2234.72  4900.4 2232.46  4928.9 2224.75  4961.5 2218.81
  4996.9 2218.71  4997.2 2218.21  5000.7 2218.21  5000.9 2218.71  5016.1 2218.82
  5038.5  2221.2  5039.3 2221.31  5044.7 2225.33  5050.9 2227.17  5067.9 2228.54
  5073.4 2233.35  5083.8 2233.34  5105.7  2235.8    5143 2238.03  5149.5 2239.09
  5160.5 2239.56  5166.2 2241.37  5171.7 2241.03  5189.5 2241.98  5194.9 2242.82
  5226.2 2244.15  5241.3 2245.84  5259.1 2246.64    5270 2248.35  5310.1 2250.17
#Mann= 4 ,-1 , 0
  4878.3     .16       0  4996.9     .07       0  5000.9     .16       0
  5038.5     .07       0
Bank Sta=4996.9,5000.9
XS Rating Curve= 0 ,0
Exp/Cntr=0.3,0.1

Type RM Length L Ch R = 1 ,16682   ,86,86,86
BEGIN DESCRIPTION:
Salt Branch 33.0
END DESCRIPTION:
XS GIS Cut Line= 3
       1378422.4      6830492.45      1378606.36      6830478.35
      1378795.74      6830392.56
#Sta/Elev= 30
  4815.5 2235.94  4819.3 2235.94  4828.1 2234.62  4858.2 2232.14  4878.3 2232.27
  4888.3 2231.19  4898.3 2229.39  4918.4 2223.75  4928.4 2221.83  4936.3 2219.41
  4941.3 2218.74  4948.5 2216.43  4958.5 2215.18  4978.6 2214.15  5040.5 2213.73
  5040.8 2213.23  5044.3 2213.23  5044.5 2213.73  5075.4 2214.69  5083.3 2215.42
  5111.8 2216.35  5119.3 2217.11  5129.4 2218.46  5141.2 2221.87  5152.2 2223.51
    5158 2225.42  5163.5 2228.46  5181.1 2230.69  5186.6 2232.02  5207.9  2232.9
#Mann= 3 ,-1 , 0
  4815.5     .07       0  5040.5     .07       0  5044.5     .07       0
Bank Sta=5040.5,5044.5
XS Rating Curve= 0 ,0
Exp/Cntr=0.3,0.1

Type RM Length L Ch R = 1 ,16596   ,65,65,65
BEGIN DESCRIPTION:
Salt Branch 33.1
END DESCRIPTION:
XS GIS Cut Line= 4
      1378399.93      6830532.42      1378594.41      6830569.75
      1378653.33      6830548.69      1378861.31      6830430.75
#Sta/Elev= 30
  4739.4 2237.87  4754.7 2236.91    4793 2232.57    4798 2232.83  4805.7  2231.7
    4826 2230.78    4850 2227.19  4894.9 2226.71  4895.2 2226.21  4898.9 2226.71
  4917.7 2230.42  4935.2 2231.04  4998.2 2232.23  5047.1 2232.15  5052.9 2231.27
  5059.4 2232.44  5068.8 2232.51  5074.5 2230.82  5090.4 2232.65  5096.1 2231.21
    5112 2232.35  5117.8 2231.37  5127.9 2232.45  5133.7 2230.71  5139.9 2231.84
  5149.5 2231.67  5155.3 2229.17  5176.9 2226.79  5198.5 2230.22  5239.1  2233.9
#Mann= 3 ,-1 , 0
  4739.4     .07       0  4894.9     .07       0  4898.9     .07       0
Bank Sta=4894.9,4898.9
XS Rating Curve= 0 ,0
Exp/Cntr=0.3,0.1

Type RM Length L Ch R = 1 ,16531   ,375,375,375
BEGIN DESCRIPTION:
Salt Branch 4096
END DESCRIPTION:
XS GIS Cut Line= 3
      1378468.91      6830626.66      1378675.16      6830607.93
      1378853.57      6830449.96
#Sta/Elev= 30
  4792.9 2230.72  4809.1 2229.02  4819.1 2226.45  4839.2 2225.04  4879.3 2223.75
  4899.4  2226.1  4909.5 2224.24  4919.5 2220.45  4939.3 2216.73  4949.6 2215.19
  4967.7 2214.87    4968 2214.37  4971.7 2214.87  4989.8 2214.92  4997.4 2216.54
  5003.2 2216.54    5007 2217.87  5027.9 2217.88  5049.6 2221.01  5056.3 2220.16
  5078.1 2222.86  5092.3 2222.58  5141.6 2225.86  5148.3 2228.72  5155.8 2229.02
  5162.5 2231.92  5176.7 2231.24    5191 2227.55  5198.5 2227.06  5238.3 2232.48
#Mann= 3 ,-1 , 0
  4792.9     .07       0  4967.7     .07       0  4971.7     .07       0
Bank Sta=4967.7,4971.7
XS Rating Curve= 0 ,0
Exp/Cntr=0.3,0.1

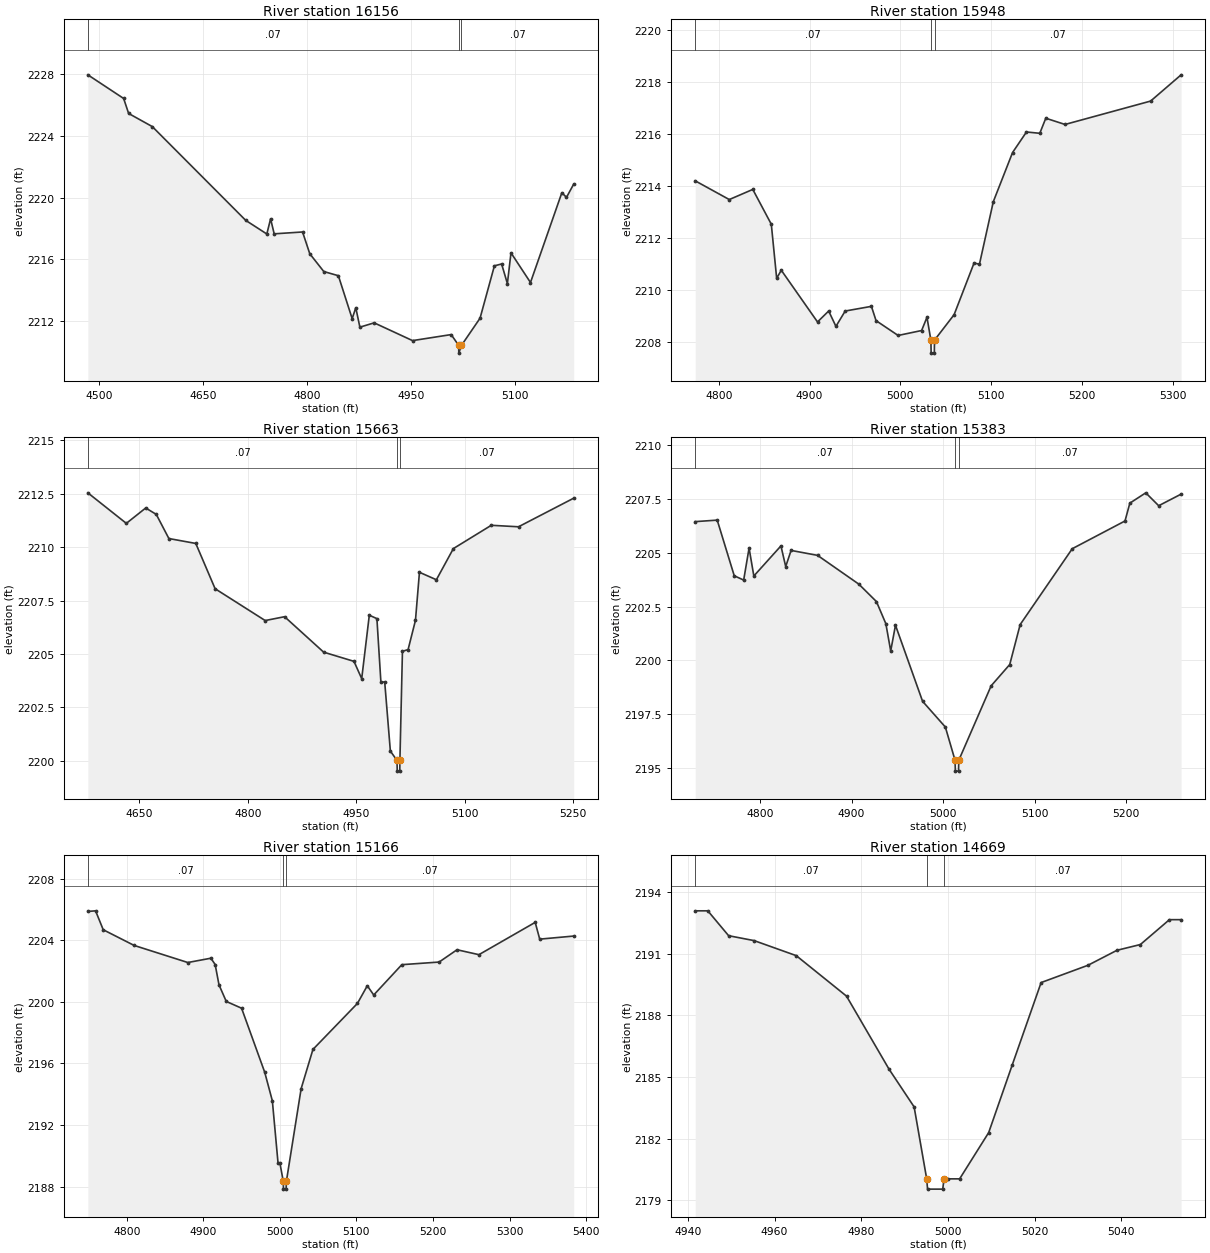
Type RM Length L Ch R = 1 ,16156   ,208,208,208
BEGIN DESCRIPTION:
Salt Branch 32.0
END DESCRIPTION:
XS GIS Cut Line= 3
      1378355.01        6830788.      1378855.28      6830915.24
      1378905.01      6830737.98
#Sta/Elev= 30
  4483.8 2227.95  4535.4 2226.42  4542.6 2225.45  4576.7  2224.6  4711.4 2218.53
  4741.8 2217.65  4747.2 2218.63  4752.4 2217.66  4793.3 2217.78  4803.7 2216.37
  4823.9 2215.22  4844.9 2214.95  4864.8 2212.17    4870 2212.88  4875.9 2211.62
  4896.5  2211.9  4951.8 2210.75  5007.5 2211.14  5018.3 2210.44  5018.5 2209.94
  5022.3 2210.44  5049.1  2212.2  5069.8 2215.59  5080.2 2215.71  5088.5 2214.44
  5093.7 2216.43  5121.8 2214.51    5167 2220.32  5173.7 2220.02  5184.1 2220.88
#Mann= 3 ,-1 , 0
  4483.8     .07       0  5018.3     .07       0  5022.3     .07       0
Bank Sta=5018.3,5022.3
XS Rating Curve= 0 ,0
Exp/Cntr=0.3,0.1

Type RM Length L Ch R = 1 ,15948   ,285,285,285
BEGIN DESCRIPTION:
Salt Branch 31.1
END DESCRIPTION:
XS GIS Cut Line= 3
      1378632.72      6831046.06      1378854.64       6831088.3
      1379018.79      6830826.04
#Sta/Elev= 30
  4774.1  2214.2  4811.6 2213.48  4837.5 2213.87  4857.9 2212.53  4863.8 2210.45
  4868.9 2210.76  4908.8 2208.77  4921.1 2209.19  4929.1  2208.6  4939.3 2209.19
  4968.2 2209.37  4973.3 2208.82  4997.6 2208.25  5023.5 2208.44  5029.4 2208.95
  5033.7 2208.07    5034 2207.57  5037.5 2207.57  5037.7 2208.07  5059.3 2209.05
  5081.3 2211.04  5087.2 2210.99  5102.5  2213.4  5123.7 2215.29    5139 2216.08
  5153.7 2216.03  5160.3 2216.61  5181.5 2216.37  5275.8 2217.27  5309.4 2218.28
#Mann= 3 ,-1 , 0
  4774.1     .07       0  5033.7     .07       0  5037.7     .07       0
Bank Sta=5033.7,5037.7
XS Rating Curve= 0 ,0
Exp/Cntr=0.3,0.1

Type RM Length L Ch R = 1 ,15663   ,280,280,280
BEGIN DESCRIPTION:
Salt Branch 31.0
END DESCRIPTION:
XS GIS Cut Line= 3
      1378654.99        6831138.      1379055.46      6831267.83
      1379155.02      6831037.96
#Sta/Elev= 30
    4579 2212.55  4632.2 2211.12    4659 2211.84  4673.6 2211.54    4691 2210.41
  4728.2 2210.18  4754.9 2208.06  4824.1 2206.57  4850.9 2206.75  4904.9 2205.09
  4946.8 2204.66  4957.5 2203.85    4968 2206.82  4978.5 2206.66    4984  2203.7
  4989.3 2203.69  4997.1 2200.46  5006.3 2200.02  5006.6 2199.52  5010.1 2199.52
  5010.3 2200.02  5013.8 2205.13  5021.6 2205.21  5031.8 2206.58  5037.3 2208.83
  5060.7 2208.48  5084.2 2209.94  5136.6 2211.03  5174.2 2210.96  5250.5  2212.3
#Mann= 3 ,-1 , 0
    4579     .07       0  5006.3     .07       0  5010.3     .07       0
Bank Sta=5006.3,5010.3
XS Rating Curve= 0 ,0
Exp/Cntr=0.3,0.1

Type RM Length L Ch R = 1 ,15383   ,217,217,217
BEGIN DESCRIPTION:
Salt Branch 30.1
END DESCRIPTION:
XS GIS Cut Line= 3
       1378813.9      6831437.56      1379075.33       6831507.8
      1379158.37      6831261.41
#Sta/Elev= 30
  4729.3 2206.45  4753.3 2206.52  4771.9 2203.93  4782.2 2203.73  4788.1 2205.22
  4793.3 2203.92  4822.9 2205.32  4828.1 2204.36    4834 2205.11  4862.9 2204.88
    4908 2203.54  4927.2 2202.73  4937.5  2201.7  4942.8 2200.43    4948 2201.63
  4977.6 2198.09  5002.5 2196.89  5013.1 2195.34  5013.4 2194.84  5016.9 2194.84
  5017.1 2195.34  5052.5 2198.81  5072.8  2199.8  5084.2 2201.66  5141.1 2205.19
  5198.7 2206.48    5204 2207.31  5221.4 2207.79  5235.5 2207.19    5260 2207.73
#Mann= 3 ,-1 , 0
  4729.3     .07       0  5013.1     .07       0  5017.1     .07       0
Bank Sta=5013.1,5017.1
XS Rating Curve= 0 ,0
Exp/Cntr=0.3,0.1

Type RM Length L Ch R = 1 ,15166   ,497,497,497
BEGIN DESCRIPTION:
Salt Branch 30.0
END DESCRIPTION:
XS GIS Cut Line= 3
      1378854.98        6831738.      1379104.76      6831715.46
      1379304.99      6831388.02
#Sta/Elev= 30
  4749.2 2205.88  4759.3 2205.92  4769.3 2204.69  4809.7 2203.67  4879.8 2202.56
  4909.9 2202.84  4915.5 2202.43  4920.5 2201.11    4930 2200.03    4950 2199.59
  4980.2 2195.43  4990.2 2193.57  4997.6 2189.54    5000 2189.54  5004.5 2188.33
  5004.7 2187.83  5008.2 2187.83  5008.5 2188.33  5027.8 2194.36  5043.2 2196.91
  5101.3  2199.9  5114.2 2201.05  5122.6 2200.45  5159.3 2202.42    5208 2202.59
  5231.4 2203.39    5260 2203.07  5333.5 2205.17  5339.4 2204.08  5383.8 2204.28
#Mann= 3 ,-1 , 0
  4749.2     .07       0  5004.5     .07       0  5008.5     .07       0
Bank Sta=5004.5,5008.5
XS Rating Curve= 0 ,0
Exp/Cntr=0.3,0.1

Type RM Length L Ch R = 1 ,14669   ,495,495,495
BEGIN DESCRIPTION:
Salt Branch 29.0
END DESCRIPTION:
XS GIS Cut Line= 3
      1379355.04      6832037.98      1379405.03      6832007.99
      1379454.99      6831988.01
#Sta/Elev= 22
  4941.7 2193.08  4944.6 2193.08  4949.4 2191.87  4955.3 2191.63    4965  2190.9
  4976.6 2188.93  4986.4 2185.38  4992.2 2183.54  4995.1 2180.04  4995.3 2179.54
  4998.8 2179.54  4999.1 2180.04    5000 2180.04  5002.7 2180.04  5009.4 2182.29
  5014.8 2185.56  5021.5 2189.59  5032.3 2190.43    5039 2191.16  5044.4 2191.44
  5051.1 2192.65  5053.8 2192.65
#Mann= 3 ,-1 , 0
  4941.7     .07       0  4995.1     .07       0  4999.1     .07       0
Bank Sta=4995.1,4999.1
XS Rating Curve= 0 ,0
Exp/Cntr=0.3,0.1

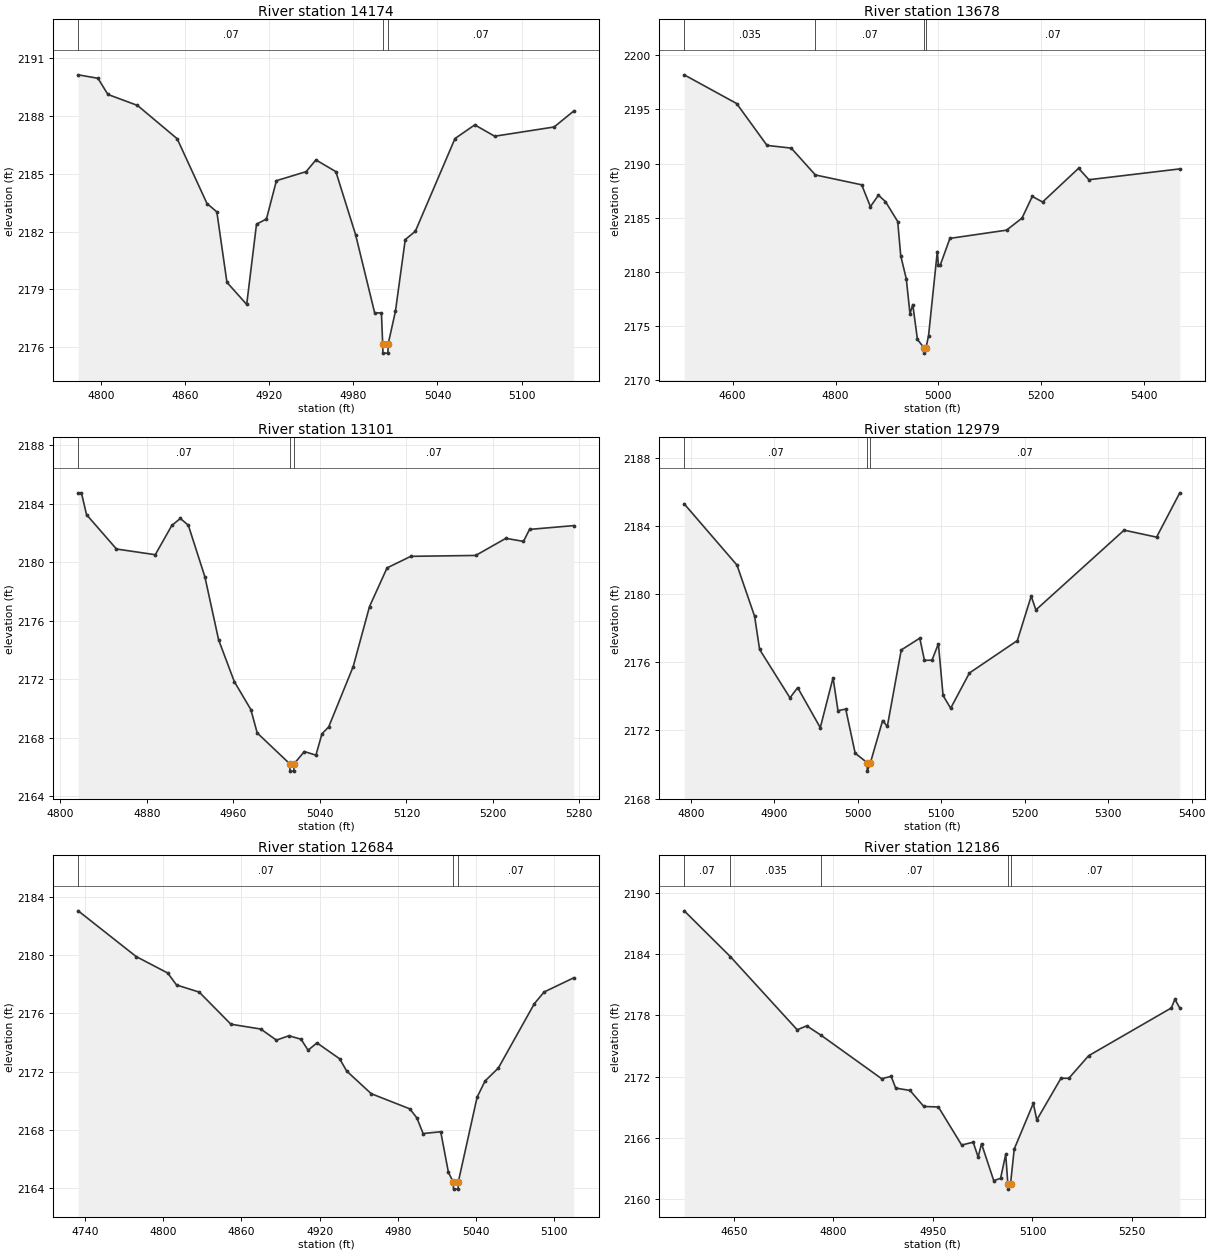
Type RM Length L Ch R = 1 ,14174   ,496,496,496
BEGIN DESCRIPTION:
Salt Branch 28.0
END DESCRIPTION:
XS GIS Cut Line= 3
      1379305.02      6832637.98      1379459.19      6832486.27
      1379554.97      6832388.03
#Sta/Elev= 30
  4783.7 2190.15  4797.8 2189.97  4804.9 2189.13    4826 2188.56  4854.3 2186.83
  4875.6 2183.46  4882.6 2183.03  4889.8 2179.37  4903.9 2178.22  4910.9 2182.39
    4918 2182.66  4925.1 2184.65  4946.3 2185.12  4953.3 2185.73  4967.5 2185.12
  4981.6 2181.84  4995.2 2177.78    5000 2177.78  5000.9 2176.19  5001.1 2175.69
  5004.6 2175.69  5004.9 2176.19    5010 2177.86    5017 2181.59  5024.2 2182.02
  5052.5 2186.84  5066.6 2187.55  5080.8 2186.96  5123.2 2187.44  5137.2 2188.27
#Mann= 3 ,-1 , 0
  4783.7     .07       0  5000.9     .07       0  5004.9     .07       0
Bank Sta=5000.9,5004.9
XS Rating Curve= 0 ,0
Exp/Cntr=0.3,0.1

Type RM Length L Ch R = 1 ,13678   ,577,577,577
BEGIN DESCRIPTION:
Salt Branch 27.0
END DESCRIPTION:
XS GIS Cut Line= 3
       1379520.7      6833196.67      1379710.53      6832740.38
       1379733.3      6832271.53
#Sta/Elev= 30
  4505.8  2198.2  4607.7 2195.55  4666.8 2191.68  4713.9 2191.43  4760.8 2188.95
  4850.9 2188.04  4867.8 2186.02  4883.4 2187.08  4897.1 2186.49  4920.9 2184.65
  4926.8 2181.48  4937.6 2179.35  4944.8 2176.12  4950.2 2176.98  4959.3 2173.75
    4972 2172.99  4972.3 2172.49    4976 2172.99  4980.9 2174.11  4997.9 2181.87
    5000 2180.63  5003.7 2180.63  5022.4 2183.09  5132.5 2183.85  5162.6 2184.96
  5182.6 2186.97  5202.6 2186.45  5272.7 2189.57  5292.7 2188.51  5469.4 2189.51
#Mann= 4 ,-1 , 0
  4505.8    .035       0  4760.8     .07       0    4972     .07       0
    4976     .07       0
Bank Sta=4972,4976
XS Rating Curve= 0 ,0
Exp/Cntr=0.3,0.1

Type RM Length L Ch R = 1 ,13101   ,122,122,122
BEGIN DESCRIPTION:
Salt Branch 26.0
END DESCRIPTION:
XS GIS Cut Line= 3
      1379954.99      6833138.01      1380110.52      6833040.44
      1380239.76      6832797.93
#Sta/Elev= 30
  4816.4 2184.74  4819.4 2184.74  4824.1 2183.25  4851.8  2180.9  4887.7 2180.51
    4903 2182.51  4910.9 2182.99  4918.3 2182.52  4933.6    2179  4946.3 2174.69
  4960.8 2171.84  4976.1 2169.93    4982 2168.33  5012.1 2166.22  5012.3 2165.72
  5015.8 2165.72  5016.1 2166.22  5025.6 2167.06  5036.3 2166.81  5041.9 2168.27
  5048.1 2168.74  5070.8 2172.87  5085.9 2176.97  5102.1 2179.61  5124.1  2180.4
  5184.1 2180.46    5212 2181.63  5228.3 2181.42  5233.9 2182.24  5274.8  2182.5
#Mann= 3 ,-1 , 0
  4816.4     .07       0  5012.1     .07       0  5016.1     .07       0
Bank Sta=5012.1,5016.1
XS Rating Curve= 0 ,0
Exp/Cntr=0.3,0.1

Type RM Length L Ch R = 1 ,12979   ,295,295,295
BEGIN DESCRIPTION:
Salt Branch 4095
END DESCRIPTION:
XS GIS Cut Line= 3
      1380020.07      6833239.14      1380195.29      6833127.25
      1380370.15      6832783.35
#Sta/Elev= 30
  4792.1 2185.29  4855.3  2181.7  4876.4  2178.7  4882.4 2176.75  4918.8 2173.91
    4928 2174.51  4955.1 2172.16  4970.4 2175.09  4976.3 2173.16  4985.6 2173.25
  4996.9 2170.66  5011.2 2170.11  5011.4 2169.61  5015.2 2170.11  5029.8 2172.58
  5035.4 2172.23  5052.1 2176.72  5074.3 2177.41  5079.9 2176.11  5088.9 2176.12
  5096.6 2177.08  5102.2 2174.05  5111.3  2173.3  5133.8 2175.37  5191.2 2177.27
  5207.8 2179.88  5213.4 2179.07  5319.1 2183.75    5358 2183.34  5385.8 2185.94
#Mann= 3 ,-1 , 0
  4792.1     .07       0  5011.2     .07       0  5015.2     .07       0
Bank Sta=5011.2,5015.2
XS Rating Curve= 0 ,0
Exp/Cntr=0.3,0.1

Type RM Length L Ch R = 1 ,12684   ,498,498,498
BEGIN DESCRIPTION:
Salt Branch 25.0
END DESCRIPTION:
XS GIS Cut Line= 3
      1380205.02      6833337.99      1380451.11      6833239.43
      1380505.02      6833137.96
#Sta/Elev= 30
  4734.9 2183.02  4779.3 2179.89  4803.5 2178.76  4810.3 2177.94  4827.7 2177.45
    4852 2175.25  4874.9 2174.92  4886.9 2174.16  4896.5 2174.46  4905.8 2174.22
  4911.2 2173.47    4918 2173.97  4935.4 2172.88  4940.8 2172.04  4959.6 2170.49
  4989.2 2169.45  4994.6 2168.83  4999.4 2167.76  5012.9 2167.88  5018.8  2165.1
  5022.4 2164.45  5022.7 2163.95  5026.2 2163.95  5026.4 2164.45  5040.8 2170.25
  5046.9 2171.36  5057.1 2172.25  5084.7 2176.66  5092.2 2177.46  5114.9 2178.43
#Mann= 3 ,-1 , 0
  4734.9     .07       0  5022.4     .07       0  5026.4     .07       0
Bank Sta=5022.4,5026.4
XS Rating Curve= 0 ,0
Exp/Cntr=0.3,0.1

Type RM Length L Ch R = 1 ,12186   ,473,473,473
BEGIN DESCRIPTION:
Salt Branch 24.0
END DESCRIPTION:
XS GIS Cut Line= 3
      1380505.03      6833787.98      1380824.84      6833508.38
       1380748.3      6833195.61
#Sta/Elev= 30
  4575.2 2188.25  4644.6 2183.77  4745.5 2176.59  4759.8 2176.98  4781.4 2176.06
  4872.7  2171.8    4887 2172.03  4893.9 2170.88  4915.4 2170.65  4936.3 2169.08
  4958.2 2169.03  4993.3  2165.3  5010.7 2165.58  5018.1 2164.12  5023.2 2165.43
  5041.6 2161.82  5051.9 2162.03  5059.7 2164.39  5062.9 2161.48  5063.1 2160.98
  5066.9 2161.48  5072.5 2164.91  5101.3 2169.39  5106.5 2167.76    5143 2171.85
  5154.8 2171.84  5184.6 2174.05  5309.2 2178.73  5314.6 2179.58    5322 2178.73
#Mann= 5 ,-1 , 0
  4575.2     .07       0  4644.6    .035       0  4781.4     .07       0
  5062.9     .07       0  5066.9     .07       0
Bank Sta=5062.9,5066.9
XS Rating Curve= 0 ,0
Exp/Cntr=0.3,0.1

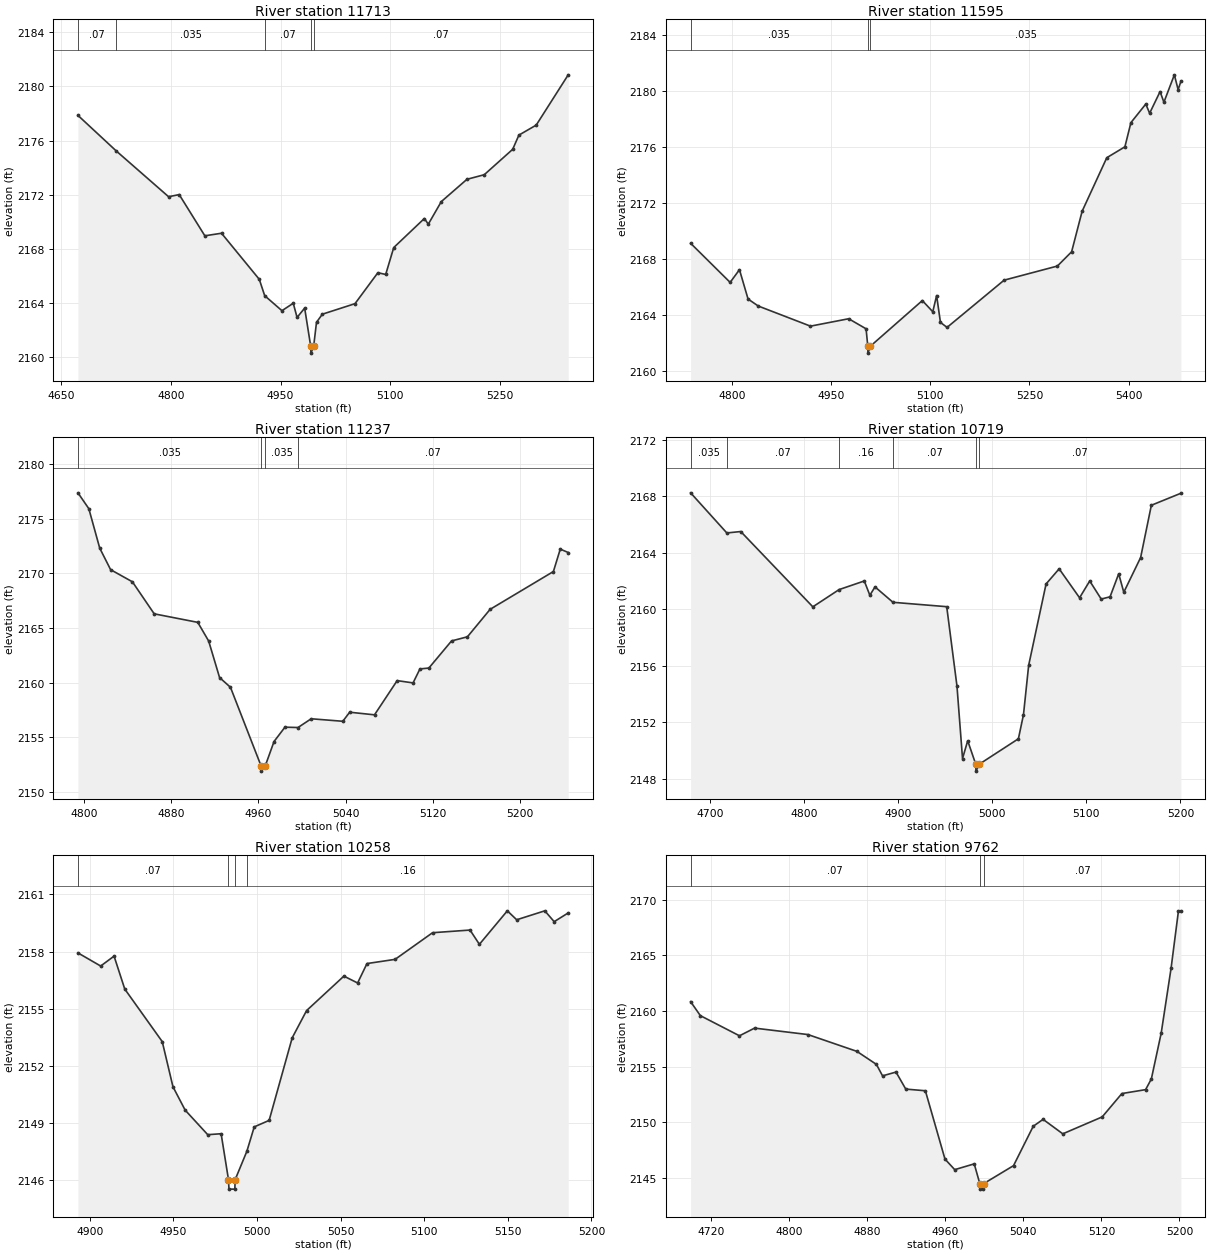
Type RM Length L Ch R = 1 ,11713   ,118,118,118
BEGIN DESCRIPTION:
Salt Branch 23.0
END DESCRIPTION:
XS GIS Cut Line= 3
      1380754.96      6833888.01      1381071.47      6833804.67
      1381205.01      6833487.97
#Sta/Elev= 30
  4672.7 2177.86  4725.3 2175.22  4796.8 2171.84  4811.3    2172  4846.4 2168.95
  4869.2 2169.14  4920.9 2165.73  4928.3 2164.52  4951.9 2163.41  4967.4 2163.96
  4972.6 2162.91    4983  2163.6  4991.3 2160.77  4991.6 2160.27  4995.3 2160.77
  4999.2 2162.55  5007.2 2163.15  5051.9 2163.93  5083.2 2166.22  5093.9 2166.09
  5104.9 2168.08  5146.8 2170.23  5152.2 2169.81    5170 2171.48  5205.1 2173.13
  5228.8 2173.47  5267.7 2175.35  5276.2  2176.4  5299.9 2177.14  5343.7 2180.86
#Mann= 5 ,-1 , 0
  4672.7     .07       0  4725.3    .035       0  4928.3     .07       0
  4991.3     .07       0  4995.3     .07       0
Bank Sta=4991.3,4995.3
XS Rating Curve= 0 ,0
Exp/Cntr=0.3,0.1

Type RM Length L Ch R = 1 ,11595   ,358,358,358
BEGIN DESCRIPTION:
Salt Branch 4094
END DESCRIPTION:
XS GIS Cut Line= 3
      1381016.45       6834110.7      1381155.44      6833888.01
      1381393.82      6833472.43
#Sta/Elev= 30
  4737.5 2169.11  4797.3 2166.31  4811.4 2167.22  4824.4 2165.12  4839.8 2164.62
  4918.8 2163.18  4976.6 2163.71  5002.9 2162.99  5005.5 2161.75  5005.7 2161.25
  5009.5 2161.75    5088 2165.01  5103.8 2164.21  5109.6 2165.37  5115.4 2163.45
  5125.4 2163.09  5211.7 2166.47  5292.3 2167.48  5313.8  2168.5  5329.7  2171.4
    5367 2175.23  5394.4 2176.01  5403.5 2177.74    5426 2179.07  5431.8 2178.41
  5447.6 2179.96  5453.4  2179.2  5469.2 2181.16  5474.9  2180.1  5479.1 2180.69
#Mann= 3 ,-1 , 0
  4737.5    .035       0  5005.5    .035       0  5009.5    .035       0
Bank Sta=5005.5,5009.5
XS Rating Curve= 0 ,0
Exp/Cntr=0.3,0.1

Type RM Length L Ch R = 1 ,11237   ,518,518,518
BEGIN DESCRIPTION:
Salt Branch 22.0
END DESCRIPTION:
XS GIS Cut Line= 3
      1381004.97        6834188.      1381210.66      6834186.01
      1381405.01      6834037.99
#Sta/Elev= 30
  4794.3 2177.36  4804.3 2175.91  4814.3  2172.3  4824.3 2170.33  4844.3 2169.22
  4864.3 2166.29  4904.3 2165.51  4914.3  2163.8  4924.3 2160.46  4934.3 2159.57
  4962.3  2152.4  4962.6  2151.9  4966.3  2152.4  4974.3 2154.61  4984.3 2155.92
  4996.3 2155.89  5008.4 2156.69  5037.4 2156.46  5043.7 2157.29  5066.5 2157.05
  5087.3 2160.18  5101.9 2159.97  5108.2 2161.25  5116.4 2161.33  5137.2 2163.81
  5151.8 2164.19  5172.6  2166.7  5230.7 2170.16    5237 2172.21  5244.3  2171.9
#Mann= 4 ,-1 , 0
  4794.3    .035       0  4962.3     .07       0  4966.3    .035       0
  4996.3     .07       0
Bank Sta=4962.3,4966.3
XS Rating Curve= 0 ,0
Exp/Cntr=0.3,0.1

Type RM Length L Ch R = 1 ,10719   ,461,461,461
BEGIN DESCRIPTION:
Salt Branch 21.0
END DESCRIPTION:
XS GIS Cut Line= 3
       1381156.3      6834355.41      1381449.25      6834485.66
       1381634.6      6834409.21
#Sta/Elev= 30
  4679.4 2168.24  4717.9  2165.4  4732.7  2165.5  4809.3 2160.17  4837.2 2161.39
    4864    2162  4869.9 2160.99  4875.4 2161.58  4894.5 2160.49  4951.6 2160.18
  4962.5 2154.56  4968.4 2149.43  4973.9 2150.69  4982.4 2149.04  4982.7 2148.54
  4986.4 2149.04  5027.8 2150.83  5033.2 2152.54  5038.7 2156.03  5057.2 2161.79
  5071.1 2162.86  5092.8 2160.81  5103.6    2162  5115.8 2160.72  5125.2 2160.88
  5134.4 2162.51  5139.8  2161.2  5157.7 2163.66  5169.1 2167.36  5200.5 2168.21
#Mann= 6 ,-1 , 0
  4679.4    .035       0  4717.9     .07       0  4837.2     .16       0
  4894.5     .07       0  4982.4     .07       0  4986.4     .07       0
Bank Sta=4982.4,4986.4
XS Rating Curve= 0 ,0
Exp/Cntr=0.3,0.1

Type RM Length L Ch R = 1 ,10258   ,496,496,496
BEGIN DESCRIPTION:
Salt Branch 20.0
END DESCRIPTION:
XS GIS Cut Line= 3
      1381504.99      6834988.01      1381571.95      6834904.55
        1381655.      6834738.01
#Sta/Elev= 30
    4893 2157.93  4906.6 2157.24  4914.6 2157.76    4921 2156.03  4943.4 2153.27
  4949.8  2150.9  4957.1 2149.67  4970.6 2148.38  4978.6 2148.43    4983 2146.02
  4983.3 2145.52  4986.8 2145.52    4987 2146.02    4994 2147.51  4998.4 2148.79
  5007.3 2149.13  5021.1 2153.47  5029.7  2154.9    5052 2156.71  5060.2 2156.35
  5065.8 2157.37  5082.6 2157.59    5105 2158.99  5127.4 2159.13    5133 2158.38
  5149.7 2160.14  5155.3 2159.67  5172.1 2160.14  5177.7 2159.57  5186.1 2160.03
#Mann= 4 ,-1 , 0
    4893     .07       0    4983     .07       0    4987     .07       0
    4994     .16       0
Bank Sta=4983,4987
XS Rating Curve= 0 ,0
Exp/Cntr=0.3,0.1

Type RM Length L Ch R = 1 ,9762    ,397,397,397
BEGIN DESCRIPTION:
Salt Branch 19.0
END DESCRIPTION:
XS GIS Cut Line= 3
        1381555.        6835188.      1381855.33      6835210.81
      1382054.99        6835238.
#Sta/Elev= 30
  4698.8 2160.85  4708.8 2159.59  4748.9 2157.78  4764.4 2158.47  4819.1 2157.89
  4869.3 2156.38  4889.3 2155.21  4895.6 2154.18  4909.4 2154.52  4919.4 2152.99
  4939.5 2152.84  4959.6  2146.7  4969.6 2145.75  4989.6 2146.27  4995.3  2144.5
  4995.5    2144  4999.1    2144  4999.4  2144.5  5029.9 2146.11  5050.1 2149.65
  5060.2 2150.27  5080.4 2148.97  5120.8 2150.49    5141 2152.59  5165.3 2152.94
  5171.2  2153.9  5181.3 2158.02  5191.4 2163.83    5199 2169.01  5201.5 2169.01
#Mann= 3 ,-1 , 0
  4698.8     .07       0  4995.3     .07       0  4999.4     .07       0
Bank Sta=4995.3,4999.4
XS Rating Curve= 0 ,0
Exp/Cntr=0.3,0.1