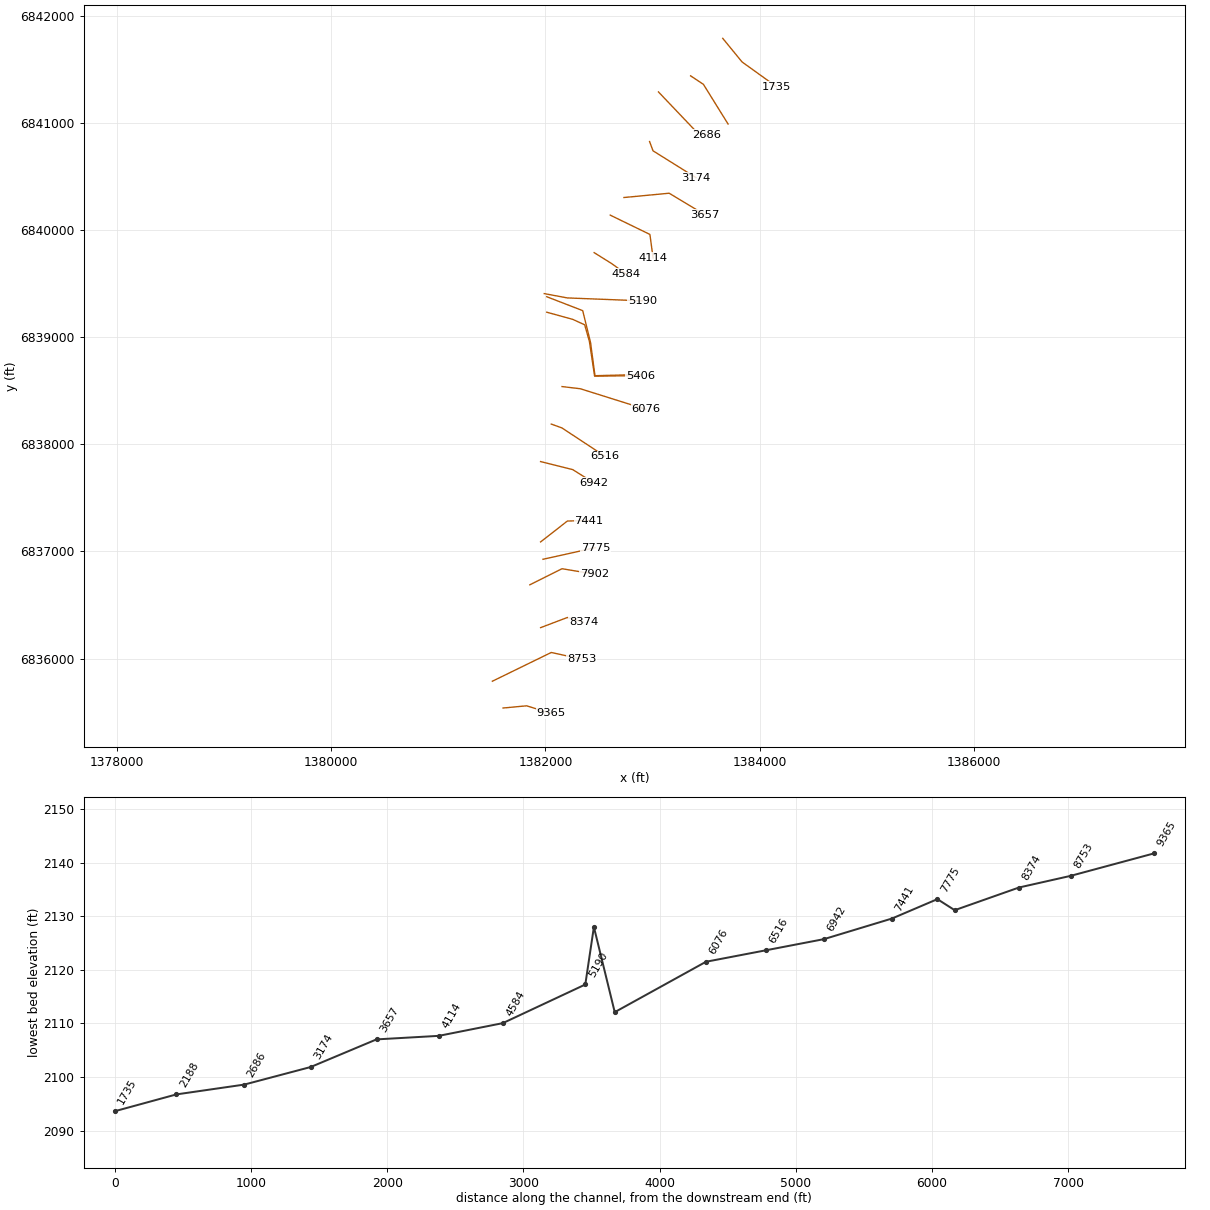
HEC-RAS study Salt Branch.prj: Salt Branch Base Level Engineering

--- Salt Branch.g01 (geometry) --- (continued)

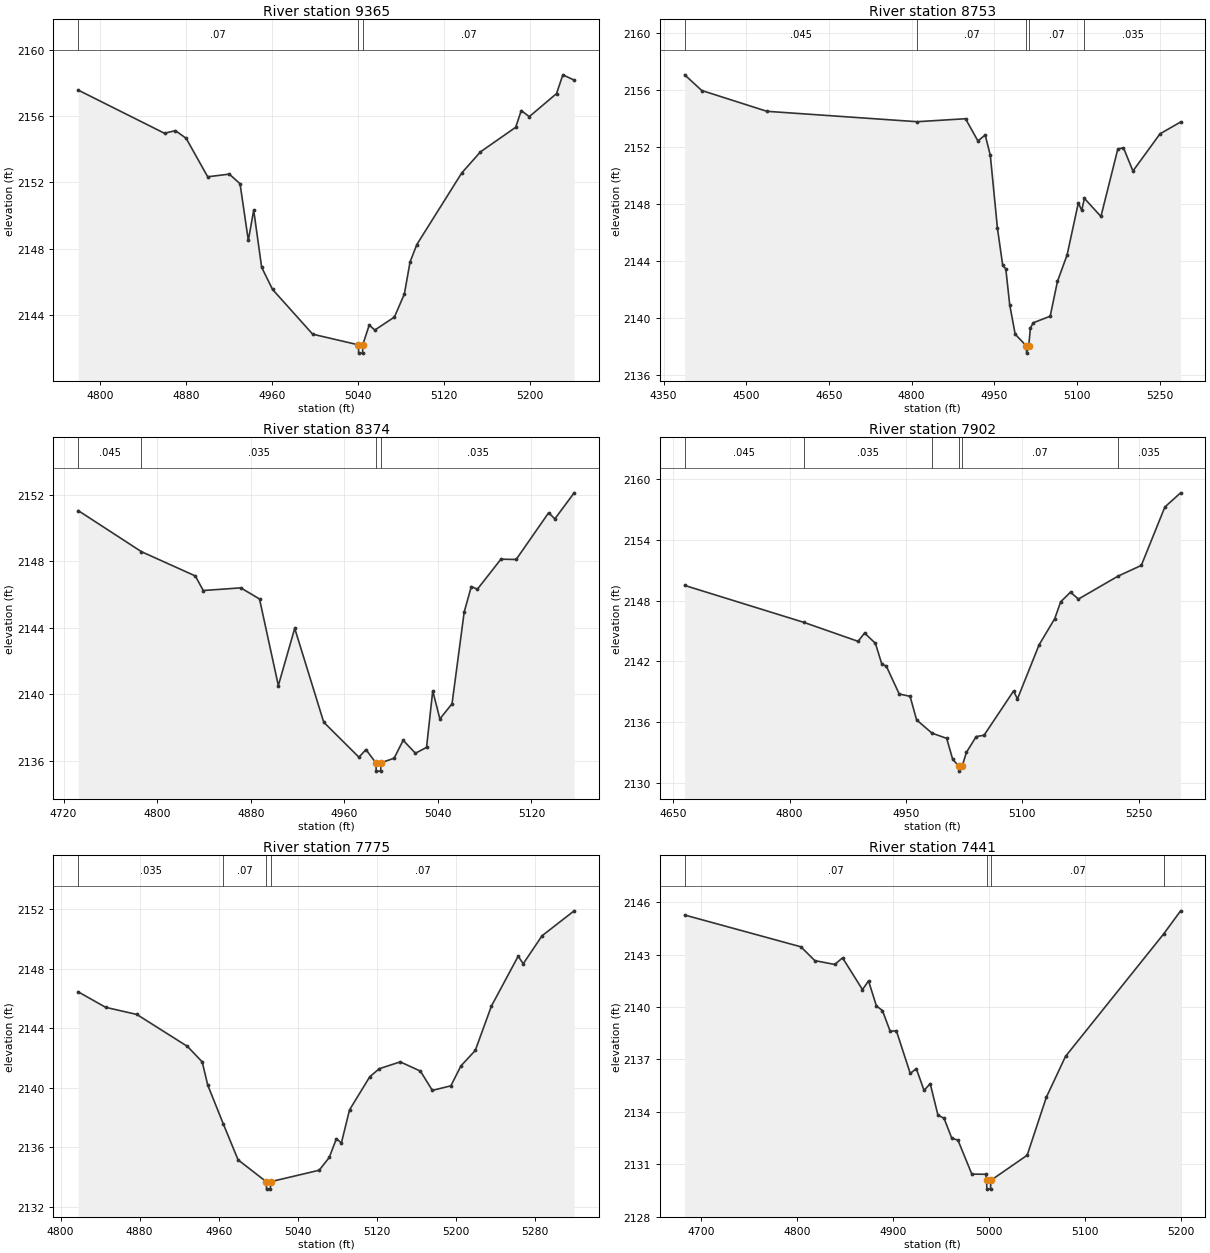
Type RM Length L Ch R = 1 ,9365    ,612,612,612
BEGIN DESCRIPTION:
Salt Branch 18.0
END DESCRIPTION:
XS GIS Cut Line= 3
      1381605.02        6835538.      1381824.47      6835558.54
      1382055.01        6835488.
#Sta/Elev= 30
  4779.6 2157.56  4859.9 2154.96    4870 2155.12    4880 2154.66  4900.1 2152.34
  4920.2  2152.5  4930.2 2151.92  4937.9 2148.51  4942.9 2150.33  4950.3 2146.89
  4960.4 2145.56  4997.8 2142.86  5040.3 2142.22  5040.6 2141.72  5044.2 2141.72
  5044.4 2142.22  5050.4 2143.41  5055.6 2143.11  5073.8 2143.89  5083.1 2145.28
  5088.4 2147.21  5094.7 2148.26  5136.5 2152.57  5153.9 2153.84  5186.7 2155.32
  5191.9 2156.33  5199.3 2155.96  5224.7 2157.35  5230.6 2158.48  5241.1 2158.16
#Mann= 3 ,-1 , 0
  4779.6     .07       0  5040.3     .07       0  5044.4     .07       0
Bank Sta=5040.3,5044.4
XS Rating Curve= 0 ,0
Exp/Cntr=0.3,0.1

Type RM Length L Ch R = 1 ,8753    ,379,379,379
BEGIN DESCRIPTION:
Salt Branch 17.0
END DESCRIPTION:
XS GIS Cut Line= 3
      1381505.02      6835788.01      1382054.61      6836056.35
       1382336.3      6835994.99
#Sta/Elev= 30
  4388.4 2157.06  4419.4 2155.96  4537.6  2154.5  4810.3 2153.77    4898 2153.98
  4920.5 2152.42  4933.7 2152.84    4943 2151.41  4955.9  2146.3  4965.5 2143.68
  4971.1 2143.44  4978.2 2140.92  4988.1 2138.86  5008.5 2138.03  5008.8 2137.53
  5012.7 2138.03  5015.7 2139.29  5020.9 2139.66  5051.6 2140.12  5064.8 2142.56
  5082.3 2144.42  5102.7 2148.07  5108.8 2147.55  5113.7 2148.39  5143.7 2147.12
  5174.4 2151.86  5184.6 2151.94  5201.8 2150.31  5250.9 2152.92  5288.3 2153.75
#Mann= 5 ,-1 , 0
  4388.4    .045       0  4810.3     .07       0  5008.5     .07       0
  5012.7     .07       0  5113.7    .035       0
Bank Sta=5008.5,5012.7
XS Rating Curve= 0 ,0
Exp/Cntr=0.3,0.1

Type RM Length L Ch R = 1 ,8374    ,472,472,472
BEGIN DESCRIPTION:
Salt Branch 16.0
END DESCRIPTION:
XS GIS Cut Line= 3
      1381955.02      6836288.01       1382205.1      6836382.96
        1382355.        6836338.
#Sta/Elev= 30
  4732.5 2151.07  4786.6 2148.59  4832.6 2147.13  4839.4 2146.25  4871.5 2146.41
  4887.5 2145.74  4903.6 2140.52  4917.6 2143.97  4942.4 2138.31  4972.5  2136.2
  4978.5 2136.66    4987 2135.86  4987.3 2135.36  4991.1 2135.36  4991.3 2135.86
  5002.6 2136.14  5010.3 2137.22  5020.8 2136.44  5030.3 2136.79  5035.6  2140.2
  5041.7 2138.51  5052.1 2139.42  5062.5 2144.96  5068.6 2146.49  5073.8 2146.33
  5093.9 2148.14  5106.9 2148.12  5134.7 2150.94    5140 2150.57  5156.5 2152.14
#Mann= 4 ,-1 , 0
  4732.5    .045       0  4786.6    .035       0    4987    .035       0
  4991.3    .035       0
Bank Sta=4987,4991.3
XS Rating Curve= 0 ,0
Exp/Cntr=0.3,0.1

Type RM Length L Ch R = 1 ,7902    ,127,127,127
BEGIN DESCRIPTION:
Salt Branch 15.0
END DESCRIPTION:
XS GIS Cut Line= 3
        1381855.        6836688.      1382154.98        6836838.
      1382455.05      6836787.99
#Sta/Elev= 30
  4664.6  2149.5  4818.5 2145.84  4888.2 2143.97  4896.6 2144.79  4910.6 2143.77
    4919 2141.68  4924.5 2141.54  4941.3 2138.76  4955.3 2138.53  4963.7  2136.2
  4983.5 2134.89  5002.5 2134.37  5010.2 2132.31  5018.1 2131.63  5018.4 2131.13
  5022.5 2131.63  5027.9 2132.98  5040.6 2134.55  5050.7 2134.68  5088.7 2139.05
  5093.8 2138.28  5121.7 2143.63  5141.9 2146.22  5149.5 2147.88  5162.2 2148.83
  5172.4 2148.15  5223.5 2150.42  5253.5 2151.48  5283.9 2157.26  5304.2 2158.66
#Mann= 6 ,-1 , 0
  4664.6    .045       0  4818.5    .035       0  4983.5     .07       0
  5018.1     .07       0  5022.5     .07       0  5223.5    .035       0
Bank Sta=5018.1,5022.5
XS Rating Curve= 0 ,0
Exp/Cntr=0.3,0.1

Type RM Length L Ch R = 1 ,7775    ,334,334,334
BEGIN DESCRIPTION:
Salt Branch 4092
END DESCRIPTION:
XS GIS Cut Line= 3
      1381977.07      6836926.14      1382154.91      6836965.31
      1382466.71      6837035.03
#Sta/Elev= 30
  4817.9 2146.46  4845.6 2145.42  4877.2 2144.94  4928.4 2142.79  4943.3 2141.75
  4948.9 2140.19  4964.8 2137.55  4979.6 2135.16  5008.1 2133.69  5008.4 2133.19
  5012.2 2133.19  5012.5 2133.69  5061.6 2134.46  5071.8 2135.32    5079 2136.58
  5084.1  2136.3  5092.3 2138.52  5112.8 2140.75  5122.4 2141.29  5143.6 2141.75
    5164 2141.13  5176.1 2139.83  5194.8 2140.14    5205 2141.48  5219.5 2142.52
  5235.8  2145.5  5262.9 2148.86    5268 2148.35    5287 2150.23  5319.5 2151.91
#Mann= 4 ,-1 , 0
  4817.9    .035       0  4964.8     .07       0  5008.1     .07       0
  5012.5     .07       0
Bank Sta=5008.1,5012.5
XS Rating Curve= 0 ,0
Exp/Cntr=0.3,0.1

Type RM Length L Ch R = 1 ,7441    ,499,499,499
BEGIN DESCRIPTION:
Salt Branch 14.0
END DESCRIPTION:
XS GIS Cut Line= 3
      1381955.02      6837088.02      1382204.95      6837283.02
      1382404.98        6837288.
#Sta/Elev= 30
    4683 2145.26  4804.2 2143.44  4818.7 2142.65  4839.5 2142.43  4847.6 2142.81
  4868.4 2140.99  4874.7 2141.49  4882.9 2140.06  4889.2 2139.79  4897.3  2138.6
  4903.7 2138.64  4918.2 2136.19  4924.5 2136.47  4932.6 2135.22    4939 2135.61
  4947.1  2133.8  4953.4 2133.63  4961.6 2132.47  4967.9 2132.38  4982.4 2130.43
  4996.8 2130.42  4997.8 2130.07  4998.1 2129.57  5001.9 2129.57  5002.2 2130.07
  5040.1 2131.51  5060.1 2134.83  5080.1 2137.17  5182.6 2144.19  5200.1  2145.5
#Mann= 4 ,-1 , 0
    4683     .07       0  4997.8     .07       0  5002.2     .07       0
  5182.6    .035       0
Bank Sta=4997.8,5002.2
XS Rating Curve= 0 ,0
Exp/Cntr=0.3,0.1

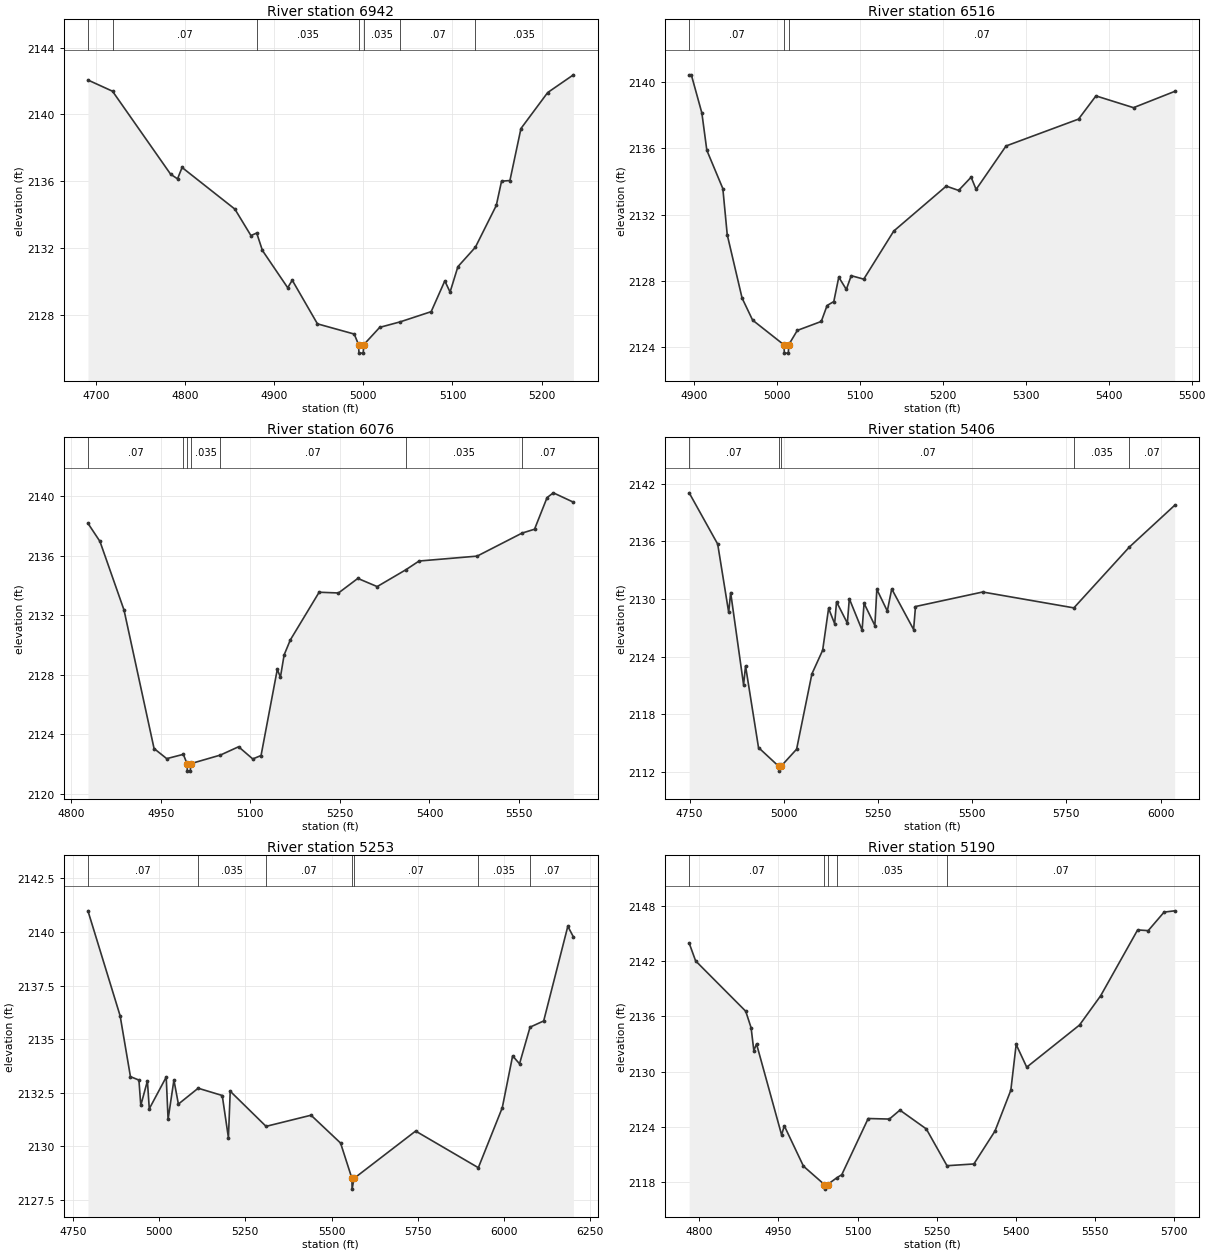
Type RM Length L Ch R = 1 ,6942    ,426,426,426
BEGIN DESCRIPTION:
Salt Branch 13.0
END DESCRIPTION:
XS GIS Cut Line= 3
      1381954.96      6837838.01      1382255.03      6837763.01
      1382454.97      6837638.02
#Sta/Elev= 30
  4690.7 2142.06  4718.3 2141.39  4783.5 2136.43  4791.3 2136.15  4796.4 2136.83
  4855.7 2134.34  4873.7 2132.76  4880.2 2132.91  4886.6 2131.87    4915 2129.64
  4920.1 2130.09  4948.4 2127.48  4989.7 2126.87  4994.6 2126.23    4995 2125.73
  4999.8 2125.73  5000.3 2126.23  5018.3 2127.27  5041.3  2127.6  5076.1 2128.21
  5091.4 2130.05  5097.3 2129.38  5106.1  2130.9  5125.7 2132.06  5149.2 2134.56
  5155.1 2136.01  5164.5 2136.05  5176.9 2139.16  5206.9 2141.31  5235.8 2142.37
#Mann= 7 ,-1 , 0
  4690.7    .035       0  4718.3     .07       0  4880.2    .035       0
  4994.6    .035       0  5000.3    .035       0  5041.3     .07       0
  5125.7    .035       0
Bank Sta=4994.6,5000.3
XS Rating Curve= 0 ,0
Exp/Cntr=0.3,0.1

Type RM Length L Ch R = 1 ,6516    ,440,440,440
BEGIN DESCRIPTION:
Salt Branch 12.0
END DESCRIPTION:
XS GIS Cut Line= 3
      1382055.02      6838187.99      1382154.55      6838151.82
      1382554.97      6837888.02
#Sta/Elev= 30
  4894.1 2140.43  4896.7 2140.43  4909.4 2138.13  4915.4 2135.88  4934.7 2133.57
    4940 2130.79  4957.9 2126.97  4970.6 2125.64  5008.4 2124.15  5008.9 2123.65
  5013.7 2123.65  5014.1 2124.15  5024.5 2125.02  5053.4 2125.56  5060.4 2126.52
  5068.5 2126.76  5074.5 2128.23  5083.6 2127.49  5089.5 2128.32  5104.6 2128.11
  5140.8 2131.01  5204.1 2133.72    5219 2133.46  5234.1 2134.26  5240.1 2133.52
  5276.2 2136.14  5363.6 2137.76  5384.6 2139.16  5429.9 2138.45  5479.5 2139.43
#Mann= 3 ,-1 , 0
  4894.1     .07       0  5008.4     .07       0  5014.1     .07       0
Bank Sta=5008.4,5014.1
XS Rating Curve= 0 ,0
Exp/Cntr=0.3,0.1

Type RM Length L Ch R = 1 ,6076    ,670,670,670
BEGIN DESCRIPTION:
Salt Branch 11.0
END DESCRIPTION:
XS GIS Cut Line= 3
      1382155.03        6838538.      1382325.55      6838517.85
      1382937.07      6838325.71
#Sta/Elev= 30
  4828.3 2138.19  4848.4 2136.97  4888.7 2132.35    4939 2123.03  4960.2 2122.35
    4988 2122.64  4994.2 2122.01  4994.7 2121.51  4999.7 2121.51  5000.2 2122.01
    5050 2122.59  5080.5 2123.15  5104.2 2122.33  5118.1 2122.56  5145.3 2128.36
  5150.5 2127.83  5156.7 2129.33  5167.1 2130.34  5215.3 2133.55  5247.7  2133.5
  5280.1 2134.48  5312.5 2133.93  5360.4 2135.06  5382.6 2135.65  5479.8 2135.98
    5555 2137.53  5575.9 2137.79  5596.9 2139.92  5607.4 2140.24    5641 2139.61
#Mann= 7 ,-1 , 0
  4828.3     .07       0    4988    .035       0  4994.2    .035       0
  5000.2    .035       0    5050     .07       0  5360.4    .035       0
    5555     .07       0
Bank Sta=4994.2,5000.2
XS Rating Curve= 0 ,0
Exp/Cntr=0.3,0.1

Type RM Length L Ch R = 1 ,5406    ,153,153,153
BEGIN DESCRIPTION:
Salt Branch 10.0
END DESCRIPTION:
XS GIS Cut Line= 6
      1382012.98      6839231.96      1382255.07       6839165.3
      1382366.49      6839114.49      1382410.25      6838960.44
      1382459.12      6838634.99      1382884.58       6838640.3
#Sta/Elev= 30
  4748.9 2141.04  4824.6 2135.71  4853.8 2128.61    4859 2130.67  4893.3 2121.08
  4898.5 2123.05  4932.9 2114.56  4986.6 2112.61  4987.1 2112.11  4992.6 2112.61
    5034 2114.39  5074.6 2122.22  5103.1 2124.67  5118.9 2129.03  5134.9 2127.44
    5140 2129.71  5168.7 2127.49  5173.9 2130.03  5207.8 2126.76    5213 2129.56
  5241.7 2127.24  5246.9 2131.01  5274.7 2128.75  5286.4 2131.05  5344.5 2126.83
  5349.5 2129.22  5527.8 2130.73  5769.8 2129.08  5916.7 2135.39  6037.2 2139.74
#Mann= 5 ,-1 , 0
  4748.9     .07       0  4986.6     .07       0  4992.6     .07       0
  5769.8    .035       0  5916.7     .07       0
Bank Sta=4986.6,4992.6
XS Rating Curve= 0 ,0
Exp/Cntr=0.3,0.1

Type RM Length L Ch R = 1 ,5253    ,63,63,63
BEGIN DESCRIPTION:
Salt Branch 9.1
END DESCRIPTION:
XS GIS Cut Line= 5
      1382012.57       6839376.5      1382348.08      6839246.72
      1382421.54       6838947.7      1382462.66      6838639.51
      1382891.16      6838650.34
#Sta/Elev= 30
    4794 2140.99  4887.3 2136.09  4917.2 2133.25  4941.8 2133.09  4947.2 2131.91
  4966.4 2133.05  4971.8 2131.75  5020.9 2133.23  5026.3 2131.26  5043.2 2133.09
  5056.2 2131.97  5113.5 2132.71  5183.3 2132.37  5201.2  2130.4  5206.4 2132.57
  5310.3 2130.93  5440.7 2131.45  5526.3 2130.15  5559.2  2128.5  5559.7    2128
  5565.2  2128.5  5743.8 2130.71  5925.6    2129    5995  2131.8    6025 2134.22
    6045 2133.85  6075.5 2135.56    6115 2135.85    6185 2140.27  6201.2 2139.77
#Mann= 7 ,-1 , 0
    4794     .07       0  5113.5    .035       0  5310.3     .07       0
  5559.2     .07       0  5565.2     .07       0  5925.6    .035       0
  6075.5     .07       0
Bank Sta=5559.2,5565.2
XS Rating Curve= 0 ,0
Exp/Cntr=0.3,0.1

Type RM Length L Ch R = 1 ,5190    ,606,606,606
BEGIN DESCRIPTION:
Salt Branch 9.0
END DESCRIPTION:
XS GIS Cut Line= 3
      1381989.68      6839405.55      1382204.95      6839365.28
      1382905.02        6839338.
#Sta/Elev= 30
    4781 2143.96  4793.2 2142.03  4888.1 2136.57  4898.3 2134.78  4903.5  2132.3
  4908.6 2133.02  4956.1 2123.15  4961.2 2124.14  4997.5 2119.76  5037.1 2117.77
  5037.6 2117.27  5043.1 2117.77  5060.9 2118.51  5070.1 2118.84  5120.1 2124.93
  5160.2 2124.87  5180.2 2125.84  5230.2  2123.8  5269.4 2119.81  5320.3    2120
  5360.3 2123.57  5390.3    2128  5400.4 2132.96  5420.4  2130.5  5520.4 2135.07
  5560.5 2138.25  5630.5 2145.39  5650.5 2145.31  5680.6 2147.32  5700.6 2147.46
#Mann= 5 ,-1 , 0
    4781     .07       0  5037.1     .07       0  5043.1     .07       0
  5060.9    .035       0  5269.4     .07       0
Bank Sta=5037.1,5043.1
XS Rating Curve= 0 ,0
Exp/Cntr=0.3,0.1

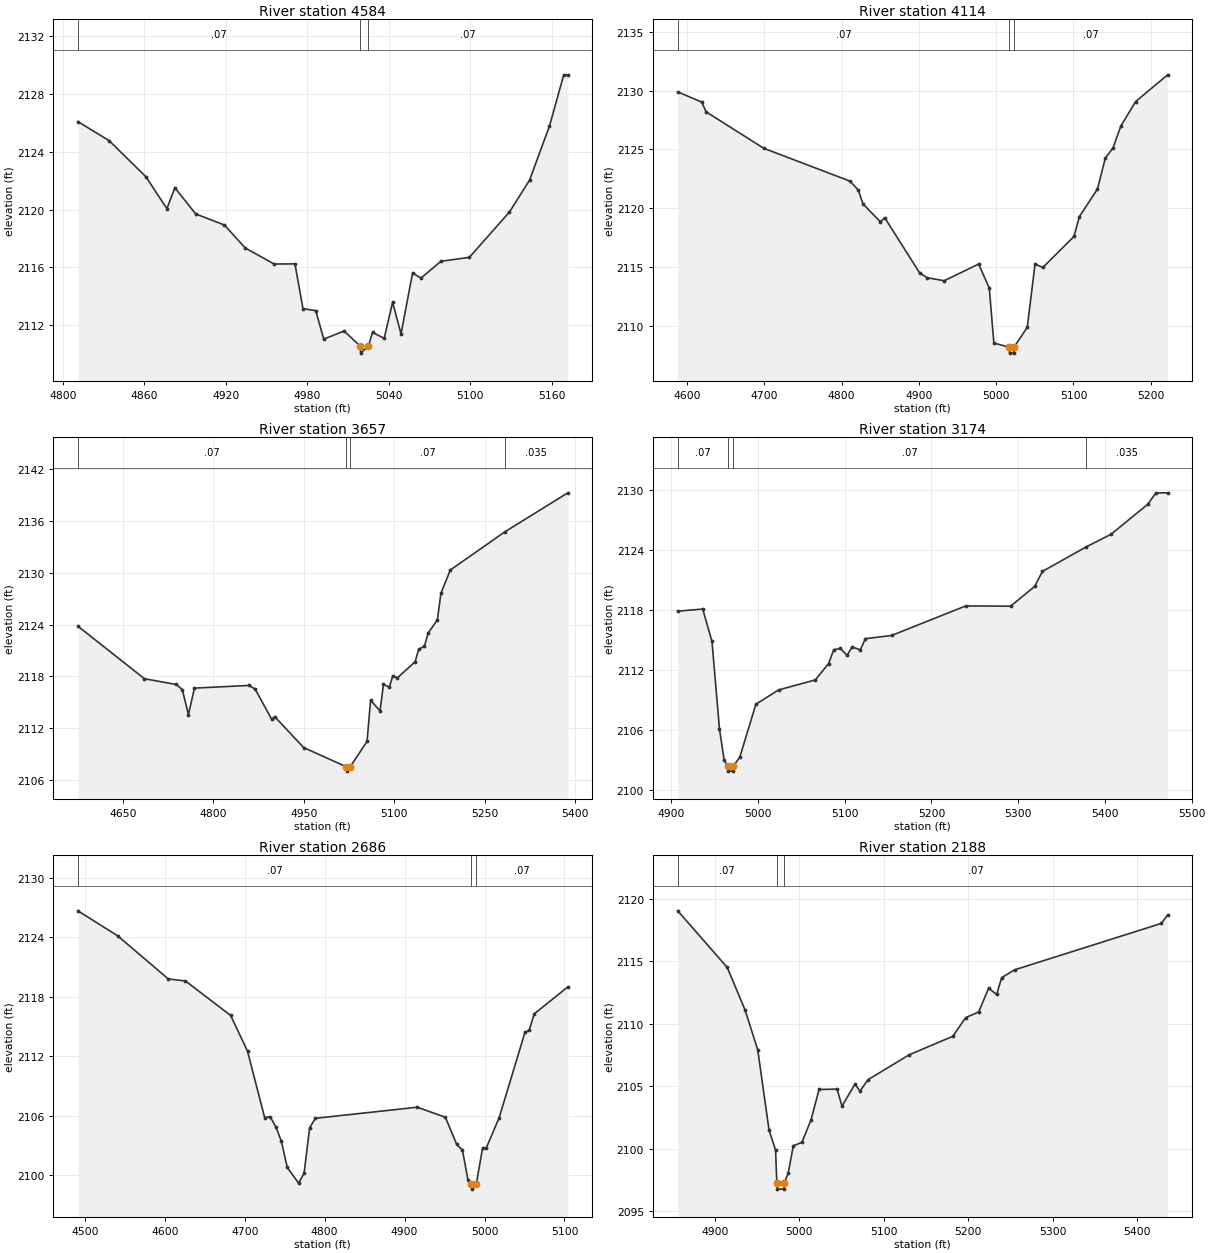
Type RM Length L Ch R = 1 ,4584    ,470,470,470
BEGIN DESCRIPTION:
Salt Branch 8.0
END DESCRIPTION:
XS GIS Cut Line= 3
      1382454.98      6839788.01      1382615.05      6839687.89
      1382754.97      6839588.02
#Sta/Elev= 30
  4811.2 2126.09  4834.2 2124.77  4861.3 2122.27  4876.7 2120.06  4882.6 2121.51
  4897.9  2119.7  4919.1 2118.93  4934.4 2117.34  4955.7 2116.23    4971 2116.24
  4976.9 2113.14  4986.3    2113  4992.2 2111.03  5007.2 2111.59  5018.9 2110.56
  5019.4 2110.06  5025.1 2110.56  5028.1  2111.5  5036.7 2111.08  5042.9 2113.58
  5049.1 2111.39  5057.6 2115.61  5063.8 2115.26  5078.5 2116.42  5099.4 2116.69
  5128.9 2119.83  5143.7 2122.03  5158.4 2125.78  5168.9 2129.33  5171.9 2129.33
#Mann= 3 ,-1 , 0
  4811.2     .07       0  5018.9     .07       0  5025.1     .07       0
Bank Sta=5018.9,5025.1
XS Rating Curve= 0 ,0
Exp/Cntr=0.3,0.1

Type RM Length L Ch R = 1 ,4114    ,457,457,457
BEGIN DESCRIPTION:
Salt Branch 7.0
END DESCRIPTION:
XS GIS Cut Line= 3
      1382604.98      6840138.01      1382975.39      6839957.84
        1383005.      6839738.02
#Sta/Elev= 30
  4588.1 2129.89  4619.2 2129.02  4624.7  2128.2  4699.3  2125.1  4810.7 2122.31
  4821.6 2121.56  4827.7 2120.37  4850.2 2118.85  4855.8  2119.2  4900.9 2114.52
  4910.6  2114.1  4932.8 2113.84  4977.3 2115.26  4991.1 2113.21    4997 2108.55
  5016.9 2108.19  5017.4 2107.69  5022.6 2107.69  5023.1 2108.19  5040.2 2109.88
  5050.3 2115.26  5060.4 2114.97  5100.7 2117.61  5107.6 2119.29    5131 2121.63
  5141.1 2124.24  5151.2 2125.14  5161.3 2126.99  5180.4 2129.07  5221.8 2131.34
#Mann= 3 ,-1 , 0
  4588.1     .07       0  5016.9     .07       0  5023.1     .07       0
Bank Sta=5016.9,5023.1
XS Rating Curve= 0 ,0
Exp/Cntr=0.3,0.1

Type RM Length L Ch R = 1 ,3657    ,483,483,483
BEGIN DESCRIPTION:
Salt Branch 6.0
END DESCRIPTION:
XS GIS Cut Line= 3
      1382732.77       6840302.3      1383155.16      6840342.56
      1383486.97       6840142.6
#Sta/Elev= 30
  4575.7 2123.81  4685.9 2117.73  4738.7 2117.06  4748.7 2116.47  4758.8 2113.58
  4768.8 2116.64  4859.2 2116.95  4869.3 2116.53  4896.8 2113.03  4901.8 2113.34
  4949.6 2109.76  5020.6 2107.53  5021.1 2107.03  5026.9 2107.53  5054.8 2110.48
  5060.6 2115.24  5076.2 2114.01    5082 2117.07  5091.7 2116.74  5097.5 2118.09
  5104.9 2117.82  5134.4 2119.69  5140.3 2121.14  5149.9 2121.48  5155.8 2122.98
  5171.3 2124.56  5177.1  2127.6  5192.7 2130.31  5282.8 2134.72  5387.4 2139.25
#Mann= 4 ,-1 , 0
  4575.7     .07       0  5020.6     .07       0  5026.9     .07       0
  5282.8    .035       0
Bank Sta=5020.6,5026.9
XS Rating Curve= 0 ,0
Exp/Cntr=0.3,0.1

Type RM Length L Ch R = 1 ,3174    ,488,488,488
BEGIN DESCRIPTION:
Salt Branch 5.0
END DESCRIPTION:
XS GIS Cut Line= 3
        1382972.      6840824.99      1383004.42      6840738.25
      1383404.98      6840488.01
#Sta/Elev= 30
  4907.4 2117.86  4936.2 2118.07  4946.9 2114.83  4955.5 2106.11  4960.9 2102.99
  4965.1 2102.38  4965.6 2101.88  4970.9 2101.88  4971.4 2102.38  4978.9 2103.26
  4997.5 2108.56  5023.6 2109.99    5066 2110.99  5081.4 2112.63  5087.3 2114.01
    5095 2114.13  5102.6 2113.45  5108.5 2114.29  5117.9 2113.99  5123.8 2115.11
    5154 2115.43  5239.4 2118.38  5291.3 2118.36    5319 2120.33  5327.9 2121.83
  5378.6 2124.29  5406.9 2125.53  5449.3 2128.53  5458.8 2129.67  5472.3 2129.68
#Mann= 4 ,-1 , 0
  4907.4     .07       0  4965.1     .07       0  4971.4     .07       0
  5378.6    .035       0
Bank Sta=4965.1,4971.4
XS Rating Curve= 0 ,0
Exp/Cntr=0.3,0.1

Type RM Length L Ch R = 1 ,2686    ,498,498,498
BEGIN DESCRIPTION:
Salt Branch 4.0
END DESCRIPTION:
XS GIS Cut Line= 3
      1383054.98      6841288.02      1383405.69      6840919.54
        1383505.        6840888.
#Sta/Elev= 30
  4491.3 2126.66  4540.9 2124.15  4604.4 2119.79  4625.8 2119.59  4682.4 2116.11
  4703.5  2112.5  4724.9 2105.82  4731.8  2105.9    4739 2104.87  4745.9 2103.41
  4753.2 2100.79  4767.4  2099.2  4774.3 2100.22  4781.2 2104.79  4788.4 2105.74
  4915.8 2106.86    4951 2105.85  4965.2 2103.11  4972.4 2102.53  4979.3 2099.53
  4983.4  2099.1  4983.9  2098.6  4989.7  2099.1  4997.6 2102.77  5002.3 2102.77
  5018.3  2105.8  5050.6 2114.41  5055.8  2114.6  5062.2 2116.27  5104.2 2118.99
#Mann= 3 ,-1 , 0
  4491.3     .07       0  4983.4     .07       0  4989.7     .07       0
Bank Sta=4983.4,4989.7
XS Rating Curve= 0 ,0
Exp/Cntr=0.3,0.1

Type RM Length L Ch R = 1 ,2188    ,453,453,453
BEGIN DESCRIPTION:
Salt Branch 3.0
END DESCRIPTION:
XS GIS Cut Line= 3
        1383355.        6841438.      1383474.78      6841358.43
      1383704.98      6840988.04
#Sta/Elev= 30
  4856.2 2119.03  4914.8  2114.5  4935.9  2111.1  4950.9 2107.91  4964.3 2101.49
    4972 2099.89  4973.5 2097.27    4974 2096.77  4981.9 2096.77  4982.4 2097.27
    4987 2098.06    4993 2100.24  5003.2 2100.51    5014 2102.32  5023.5 2104.74
  5044.8 2104.77  5050.6 2103.41    5066 2105.17  5071.9 2104.61  5081.4 2105.52
    5130 2107.51  5181.7 2108.99  5197.1 2110.49  5212.4 2110.94  5224.2 2112.84
  5233.7 2112.34  5239.6 2113.68  5254.9 2114.31  5428.5 2118.02  5436.1 2118.69
#Mann= 3 ,-1 , 0
  4856.2     .07       0  4973.5     .07       0  4982.4     .07       0
Bank Sta=4973.5,4982.4
XS Rating Curve= 0 ,0
Exp/Cntr=0.3,0.1

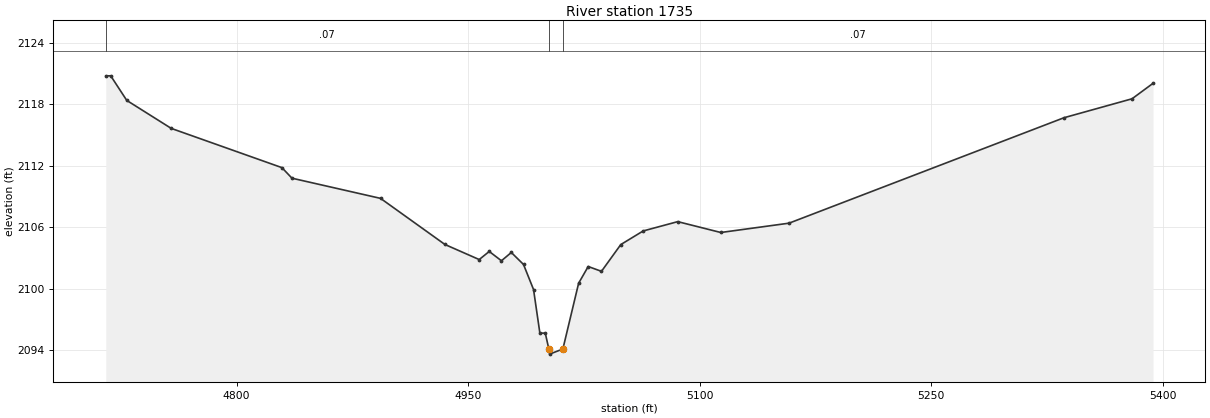
Type RM Length L Ch R = 1 ,1735    ,489,489,489
BEGIN DESCRIPTION:
Salt Branch 2.0
END DESCRIPTION:
XS GIS Cut Line= 3
        1383655.      6841788.01      1383835.28      6841567.66
      1384155.04      6841337.97
#Sta/Elev= 30
  4715.3 2120.79  4718.5 2120.79  4728.9 2118.39  4757.7 2115.66  4829.4 2111.83
  4835.9  2110.8  4893.3 2108.83    4935 2104.33  4957.2 2102.86  4963.7 2103.65
  4971.6 2102.74    4978 2103.55  4985.9 2102.38  4992.4 2099.93  4996.5 2095.68
    5000 2095.68  5002.3 2094.13  5002.8 2093.63  5011.4 2094.13  5021.6 2100.55
  5027.8 2102.18  5036.4 2101.71  5048.9 2104.32  5063.4 2105.65  5085.8 2106.56
  5113.7  2105.5  5157.9 2106.41    5336  2116.7  5380.1 2118.55  5393.7 2120.06
#Mann= 3 ,-1 , 0
  4715.3     .07       0  5002.3     .07       0  5011.4     .07       0
Bank Sta=5002.3,5011.4
XS Rating Curve= 0 ,0
Exp/Cntr=0.3,0.1