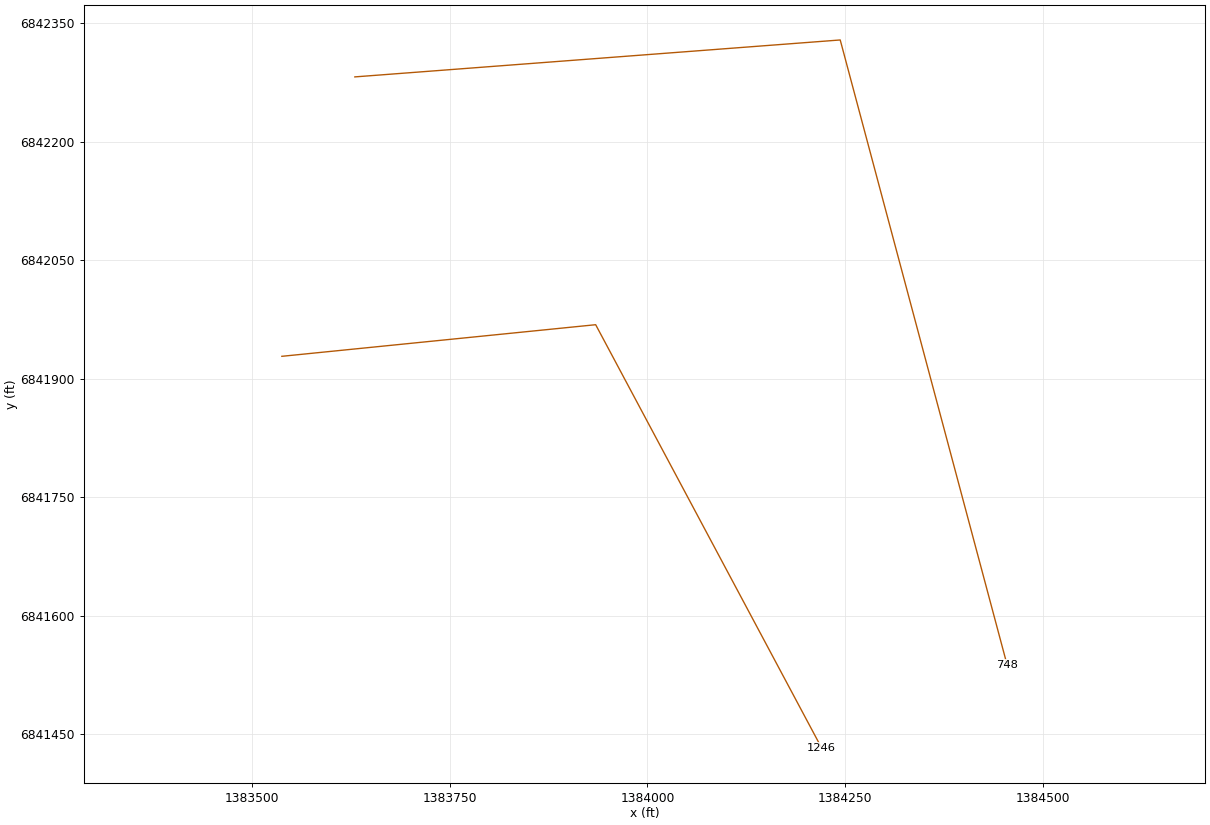
HEC-RAS study Salt Branch.prj: Salt Branch Base Level Engineering

--- Salt Branch.g01 (geometry) --- (continued)

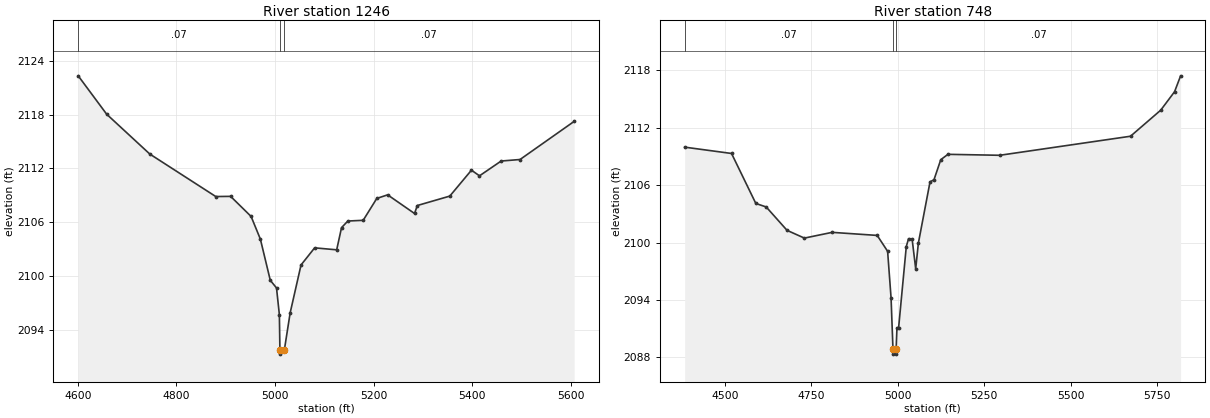
Type RM Length L Ch R = 1 ,1246    ,498,498,498
BEGIN DESCRIPTION:
Salt Branch 1.0
END DESCRIPTION:
XS GIS Cut Line= 3
      1383537.55      6841928.26      1383934.54      6841968.24
      1384220.12      6841433.29
#Sta/Elev= 30
    4601 2122.33  4658.7 2118.05  4746.1 2113.61  4879.9 2108.87    4910 2108.89
  4951.5 2106.65  4970.3 2104.12  4990.4 2099.53    5003 2098.68  5008.8  2095.7
  5009.9  2091.8  5010.4  2091.3    5019  2091.8  5030.7 2095.91  5052.7 2101.24
  5080.3 2103.15    5125 2102.93  5134.8  2105.4  5147.6 2106.14  5178.7 2106.22
  5206.3 2108.66  5228.3 2109.06  5282.8 2106.98  5288.5 2107.87  5354.3 2108.92
  5398.2 2111.81  5414.5 2111.18  5458.4 2112.83  5496.7    2113  5606.4 2117.25
#Mann= 3 ,-1 , 0
    4601     .07       0  5009.9     .07       0    5019     .07       0
Bank Sta=5009.9,5019
XS Rating Curve= 0 ,0
Exp/Cntr=0.3,0.1

Type RM Length L Ch R = 1 ,748     ,0,0,0
BEGIN DESCRIPTION:
Salt Branch 588
END DESCRIPTION:
XS GIS Cut Line= 3
      1383629.88      6842281.73       1384243.9      6842328.45
      1384455.01      6841537.96
#Sta/Elev= 30
  4384.2 2109.96  4519.7  2109.3  4589.9 2104.08    4620 2103.71  4680.2 2101.27
  4730.3 2100.46  4810.6 2101.06  4940.9 2100.74    4971 2099.08    4981 2094.19
  4986.5 2088.84    4987 2088.34  4995.1 2088.34  4995.6 2088.84    4998  2091.1
  5002.8  2091.1    5025 2099.58  5031.5  2100.4  5041.9 2100.34  5052.2 2097.25
  5059.9 2099.93  5093.6 2106.33  5105.1 2106.56  5124.7 2108.65  5145.4 2109.21
  5295.2 2109.11  5673.3  2111.1  5760.6 2113.82  5800.7 2115.75  5818.2 2117.41
#Mann= 3 ,-1 , 0
  4384.2     .07       0  4986.5     .07       0  4995.6     .07       0
Bank Sta=4986.5,4995.6
XS Rating Curve= 0 ,0
Exp/Cntr=0.3,0.1

Chan Stop Cuts=-1
Use User Specified Reach Order=0
Composite Channel Slope=5