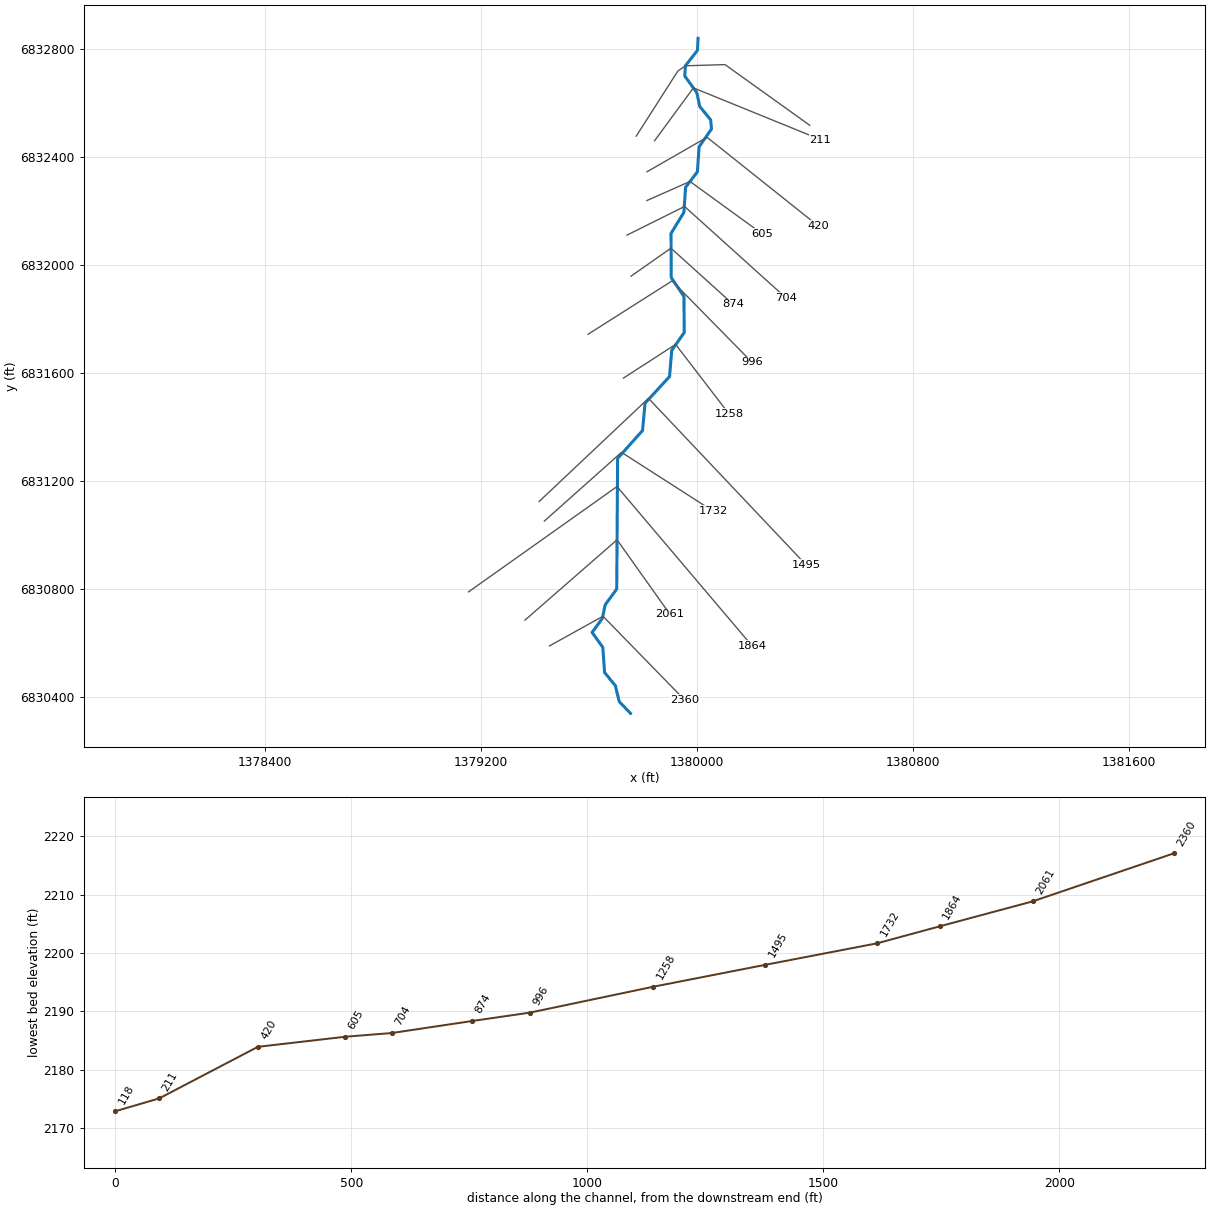
--- Salt Branch Trib1.prj (project) ---

Proj Title=Salt Branch Trib1 Base Level Engineering
Current Plan=p01
Default Exp/Contr=0.3,0.1
English Units
Geom File=g01
Flow File=f01
Plan File=p01
Y Axis Title=Elevation
X Axis Title(PF)=Main Channel Distance
X Axis Title(XS)=Station
BEGIN DESCRIPTION:
Salt Branch Trib1
END DESCRIPTION:
DSS Export Rating Curves= 0
DSS Export Rating Curve Sorted= 0
DSS Export Volume Flow Curves= 0
DXF OffsetX= 0
DXF OffsetY= 0
DXF ScaleX= 1
DXF ScaleY= 10

--- Salt Branch Trib1.p01 (plan) ---

Plan Title=Multiple Run
Short Identifier=Multiple
Geom File=g01
Flow File=f01
Subcritical Flow
K Sum by GR= 0
Std Step Tol= 0.01
Critical Tol= 0.01
Num of Std Step Trials= 20
Max Error Tol= 0.3
Flow Tol Ratio= 0.001
Split Flow NTrial= 30
Split Flow Tol= 0.02
Split Flow Ratio= 0.02
Log Output Level= 0
Friction Slope Method= 1
Unsteady Friction Slope Method= 2
Unsteady Bridges Friction Slope Method= 1
Parabolic Critical Depth
Global Vel Dist=  1 , 1 , 1
Global Log Level= 0
CheckData=True
Encroach Param= -1, 0, 0, 0
BEGIN DESCRIPTION:
Multiple Run
END DESCRIPTION:

--- Salt Branch Trib1.f01 (steady flow) ---

Flow Title=Multiple
Program Version=4.10
Number of Profiles= 7
Profile Names=10-year,25-year,50-year,1pct_min,100-year,1pct_plu,500-year
River Rch & RM=Salt Branch Trib,Reach-1         ,2360
      79     104     124      74     148     295     211
Boundary for River Rch & Prof#=Salt Branch Trib,Reach-1         , 1
Up Type= 0
Dn Type= 3
Dn Slope=0.018
Boundary for River Rch & Prof#=Salt Branch Trib,Reach-1         , 2
Up Type= 0
Dn Type= 3
Dn Slope=0.018
Boundary for River Rch & Prof#=Salt Branch Trib,Reach-1         , 3
Up Type= 0
Dn Type= 3
Dn Slope=0.018
Boundary for River Rch & Prof#=Salt Branch Trib,Reach-1         , 4
Up Type= 0
Dn Type= 3
Dn Slope=0.018
Boundary for River Rch & Prof#=Salt Branch Trib,Reach-1         , 5
Up Type= 0
Dn Type= 3
Dn Slope=0.018
Boundary for River Rch & Prof#=Salt Branch Trib,Reach-1         , 6
Up Type= 0
Dn Type= 3
Dn Slope=0.018
Boundary for River Rch & Prof#=Salt Branch Trib,Reach-1         , 7
Up Type= 0
Dn Type= 3
Dn Slope=0.018
DSS Import GetInterval= 0
DSS Import GetPeak= 0
DSS Import FillOption= 0

--- Salt Branch Trib1.g01 (geometry) ---

Geom Title=Existing Conditions
Program Version=4.10

River Reach=Salt Branch Trib,Reach-1
Reach XY= 30
        1379755.        6830338.      1379712.91      6830381.85
      1379698.97      6830440.22      1379658.81      6830489.58
      1379652.33      6830582.51      1379612.53      6830638.01
      1379650.58      6830689.64      1379661.09      6830740.17
       1379703.8       6830798.5      1379707.07      6831282.14
      1379799.46      6831385.58      1379808.63       6831486.5
      1379899.46      6831585.58      1379907.47      6831682.43
       1379953.8      6831748.51      1379952.75      6831882.06
      1379905.68      6831951.92       1379904.9      6832115.31
      1379952.53      6832193.57      1379958.85       6832286.4
      1380002.53      6832343.57      1380008.89      6832436.42
      1380054.76       6832502.1      1380051.66      6832536.28
      1380011.15       6832585.8      1380000.78      6832636.28
      1379955.72      6832698.68      1379958.15      6832736.32
      1380002.84      6832793.78        1380005.        6832838.

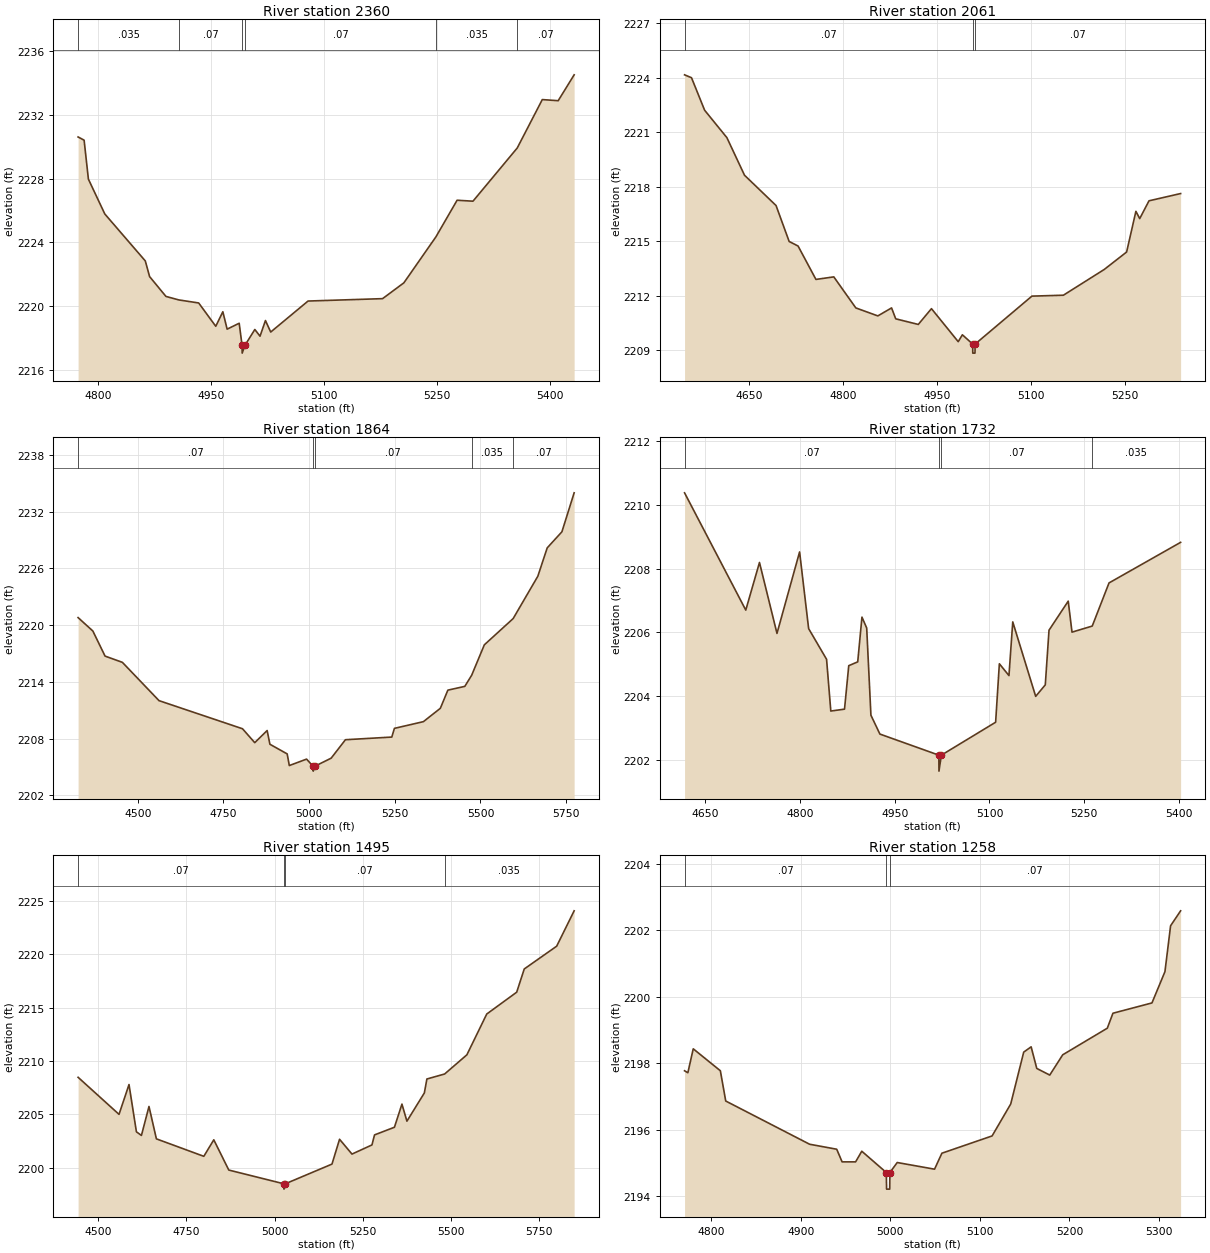
Type RM Length L Ch R = 1 ,2360    ,299,299,299
BEGIN DESCRIPTION:
Salt Branch Trib1 3.0
END DESCRIPTION:
XS GIS Cut Line= 3
        1379455.        6830588.        1379653.      6830697.78
      1379954.98      6830388.02
#Sta/Elev= 30
  4773.6  2230.6  4781.6  2230.4  4787.3 2227.96  4809.1 2225.78  4862.9 2222.84
  4868.6 2221.86  4890.3 2220.62  4907.4  2220.4  4933.8 2220.21  4956.5 2218.75
  4965.9 2219.66  4971.6 2218.57  4987.6 2218.94  4991.4 2217.57  4991.6 2217.07
  4995.4 2217.57  5008.4 2218.55  5015.3 2218.13  5022.5 2219.11  5029.5 2218.39
  5079.1 2220.33  5178.1 2220.48  5206.4 2221.47    5249 2224.35  5277.1 2226.64
  5298.2 2226.58    5357 2229.91  5390.3 2232.94  5411.4 2232.87  5432.6 2234.49
#Mann= 6 ,-1 , 0
  4773.6    .035       0  4907.4     .07       0  4991.4     .07       0
  4995.4     .07       0    5249    .035       0    5357     .07       0
Bank Sta=4991.4,4995.4
XS Rating Curve= 0 ,0
Exp/Cntr=0.3,0.1

Type RM Length L Ch R = 1 ,2061    ,197,197,197
BEGIN DESCRIPTION:
Salt Branch Trib1 4181
END DESCRIPTION:
XS GIS Cut Line= 3
      1379364.13      6830683.52      1379705.01       6830980.8
      1379901.14      6830704.67
#Sta/Elev= 30
  4547.7 2224.17  4558.8 2224.01  4579.7 2222.22  4615.2 2220.71  4643.3 2218.64
  4693.6 2216.97  4714.5 2214.99  4728.7 2214.74  4757.2  2212.9  4785.7 2213.04
  4820.8 2211.33  4855.9 2210.89  4877.8 2211.33  4884.4 2210.73  4920.4 2210.42
  4941.4 2211.29  4984.1 2209.47  4990.7 2209.85  5007.1 2209.34  5007.3 2208.84
  5010.8 2208.84  5011.1 2209.34  5101.6 2211.98  5151.8 2212.03    5217 2213.45
  5252.6 2214.41  5267.4 2216.65  5273.5 2216.25  5288.3 2217.23  5338.7 2217.63
#Mann= 3 ,-1 , 0
  4547.7     .07       0  5007.1     .07       0  5011.1     .07       0
Bank Sta=5007.1,5011.1
XS Rating Curve= 0 ,0
Exp/Cntr=0.3,0.1

Type RM Length L Ch R = 1 ,1864    ,132,132,132
BEGIN DESCRIPTION:
Salt Branch Trib1 2.0
END DESCRIPTION:
XS GIS Cut Line= 3
      1379155.01      6830788.01      1379704.95      6831178.02
      1380204.99      6830588.01
#Sta/Elev= 30
  4325.8 2220.79  4368.9 2219.37  4404.5 2216.72    4455 2216.06    4562 2212.01
  4805.6 2209.04  4841.3 2207.57  4877.5 2208.85  4885.6  2207.4    4936 2206.38
  4942.2 2205.15  4992.6 2205.83  5011.8 2205.06    5012 2204.56  5015.8 2205.06
  5064.3 2205.93    5106 2207.88  5241.2 2208.16  5248.9 2209.08  5333.5 2209.79
  5382.9  2211.2  5404.9 2213.12  5454.3 2213.52  5474.3 2214.69  5511.3 2217.91
  5595.5 2220.69  5667.4 2225.16  5694.8 2228.16  5737.7 2229.86  5773.4 2233.98
#Mann= 5 ,-1 , 0
  4325.8     .07       0  5011.8     .07       0  5015.8     .07       0
  5474.3    .035       0  5595.5     .07       0
Bank Sta=5011.8,5015.8
XS Rating Curve= 0 ,0
Exp/Cntr=0.3,0.1

Type RM Length L Ch R = 1 ,1732    ,237,237,237
BEGIN DESCRIPTION:
Salt Branch Trib1 4180
END DESCRIPTION:
XS GIS Cut Line= 3
      1379435.76      6831050.28      1379721.47      6831304.75
      1380060.34      6831087.38
#Sta/Elev= 30
  4617.4 2210.37  4714.3  2206.7    4736 2208.19  4763.7 2205.97  4799.5 2208.52
  4813.8 2206.12  4842.2 2205.16  4848.9 2203.54  4870.6  2203.6  4877.3 2204.96
  4891.5 2205.08  4898.2 2206.48  4905.7 2206.14  4912.4 2203.41  4926.6 2202.82
  5019.9 2202.16  5020.1 2201.66  5023.9 2202.16  5109.8 2203.19  5115.7 2205.02
  5130.9 2204.65  5136.9 2206.33  5173.2    2204  5188.4 2204.36  5194.3 2206.07
  5224.7 2206.98  5230.7 2206.01  5262.7  2206.2  5289.3 2207.55  5402.6 2208.82
#Mann= 4 ,-1 , 0
  4617.4     .07       0  5019.9     .07       0  5023.9     .07       0
  5262.7    .035       0
Bank Sta=5019.9,5023.9
XS Rating Curve= 0 ,0
Exp/Cntr=0.3,0.1

Type RM Length L Ch R = 1 ,1495    ,237,237,237
BEGIN DESCRIPTION:
Salt Branch Trib1 1.0
END DESCRIPTION:
XS GIS Cut Line= 3
      1379416.43       6831122.7      1379821.49      6831504.74
      1380404.98      6830888.02
#Sta/Elev= 30
  4443.2 2208.47  4559.2 2204.99  4587.5 2207.79  4608.5 2203.35  4622.7 2203.01
  4644.1 2205.73  4665.1 2202.69  4799.5 2201.05  4827.8  2202.6  4870.3 2199.76
  5026.4 2198.47  5026.7 2197.97  5030.4 2198.47  5162.7 2200.32  5184.2 2202.65
  5219.4 2201.26    5276 2202.12  5283.3 2203.06  5339.7 2203.78    5361 2205.95
  5375.1 2204.35  5424.5    2207  5431.7 2208.31    5482 2208.78    5545 2210.58
  5601.3 2214.41  5686.2 2216.46  5707.6 2218.64  5799.5 2220.78    5849  2224.1
#Mann= 4 ,-1 , 0
  4443.2     .07       0  5026.4     .07       0  5030.4     .07       0
    5482    .035       0
Bank Sta=5026.4,5030.4
XS Rating Curve= 0 ,0
Exp/Cntr=0.3,0.1

Type RM Length L Ch R = 1 ,1258    ,262,262,262
BEGIN DESCRIPTION:
Salt Branch Trib1 4179
END DESCRIPTION:
XS GIS Cut Line= 3
      1379728.71      6831579.78      1379921.92      6831704.56
      1380119.32      6831447.38
#Sta/Elev= 30
    4770 2197.78  4773.7 2197.72  4779.7 2198.44    4810 2197.78    4816 2196.87
  4909.7 2195.57    4940 2195.42    4946 2195.04  4961.1 2195.04    4968 2195.36
  4995.4 2194.72  4995.7 2194.22  4999.2 2194.22  4999.4 2194.72  5007.6 2195.02
  5049.3 2194.82  5057.5  2195.3  5113.6 2195.82  5134.4 2196.78  5148.9 2198.34
  5157.2  2198.5  5163.5 2197.85    5178 2197.65  5192.5 2198.26  5242.3 2199.06
  5248.6 2199.51  5292.2 2199.82  5306.7 2200.76    5313 2202.14  5324.2 2202.59
#Mann= 3 ,-1 , 0
    4770     .07       0  4995.4     .07       0  4999.4     .07       0
Bank Sta=4995.4,4999.4
XS Rating Curve= 0 ,0
Exp/Cntr=0.3,0.1

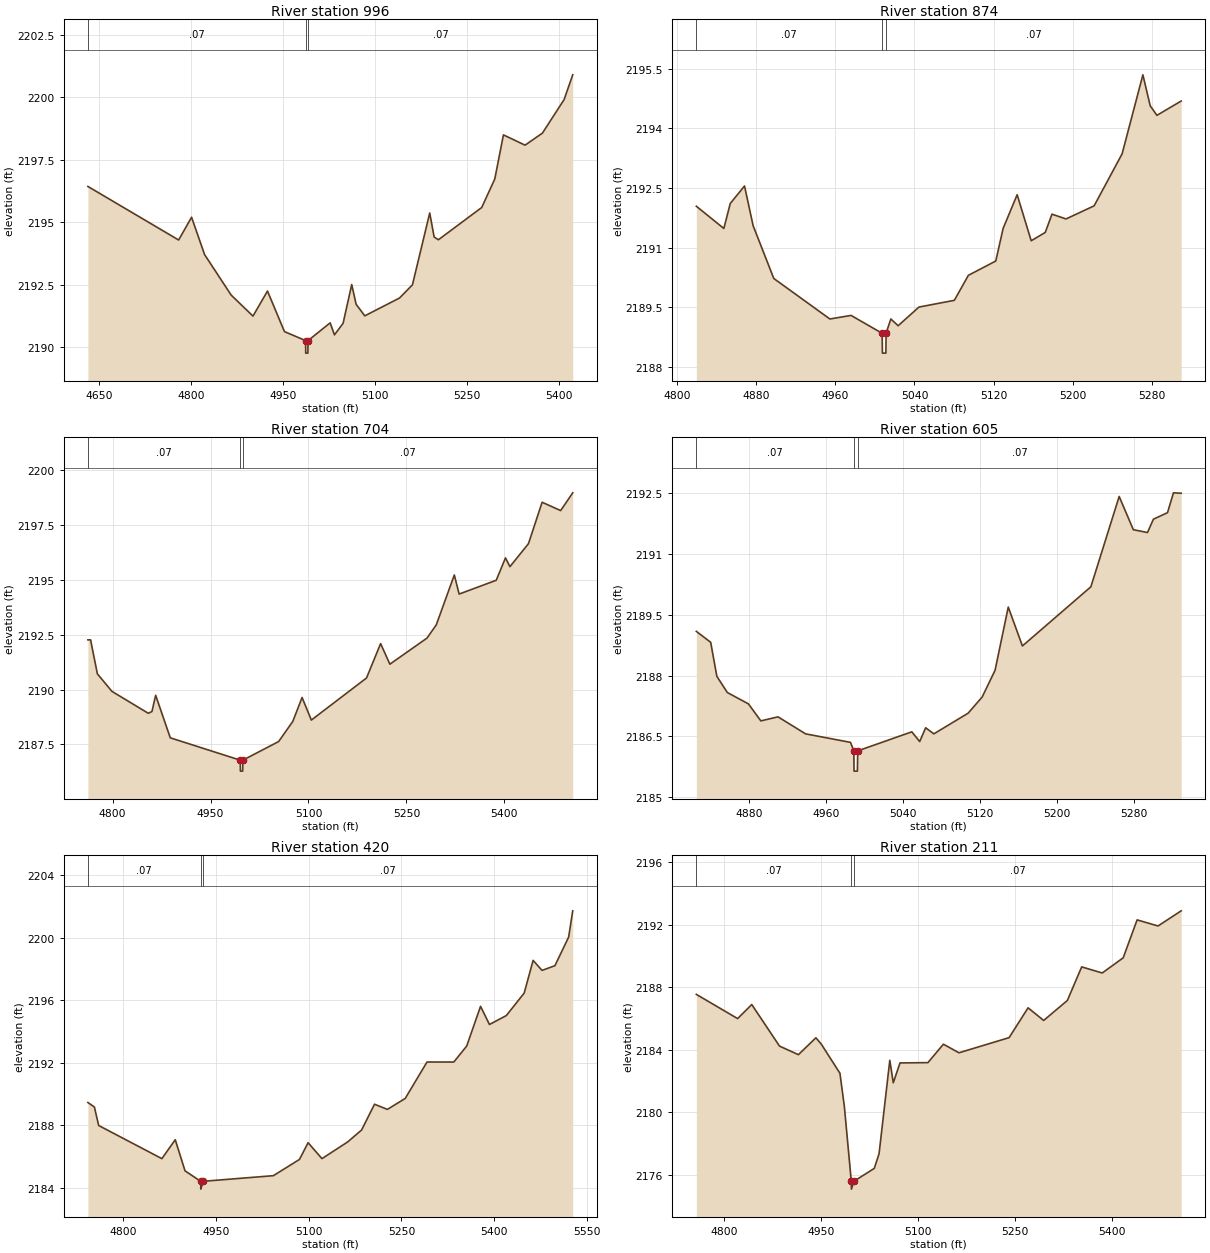
Type RM Length L Ch R = 1 ,996     ,122,122,122
BEGIN DESCRIPTION:
Salt Branch Trib1 2716
END DESCRIPTION:
XS GIS Cut Line= 3
      1379597.59      6831742.01      1379908.78      6831939.57
      1380204.99      6831638.01
#Sta/Elev= 30
  4631.4 2196.43  4779.5 2194.29  4800.6  2195.2  4821.8 2193.71  4865.2 2192.09
  4900.8 2191.25  4924.5 2192.25  4952.2 2190.63  4986.7 2190.27  4986.9 2189.77
  4990.4 2189.77  4990.7 2190.27  5026.8 2190.98  5033.8  2190.5  5047.9 2190.96
    5062 2192.51  5069.2 2191.72  5083.3 2191.26  5139.9 2191.97  5161.1  2192.5
  5189.3 2195.37  5196.5 2194.41  5203.5  2194.3  5274.2 2195.59  5295.5 2196.73
  5309.6 2198.49  5344.9 2198.08  5373.2 2198.56  5408.6  2199.9  5422.7 2200.89
#Mann= 3 ,-1 , 0
  4631.4     .07       0  4986.7     .07       0  4990.7     .07       0
Bank Sta=4986.7,4990.7
XS Rating Curve= 0 ,0
Exp/Cntr=0.3,0.1

Type RM Length L Ch R = 1 ,874     ,170,170,170
BEGIN DESCRIPTION:
Salt Branch Trib1 4184
END DESCRIPTION:
XS GIS Cut Line= 3
      1379756.87      6831957.34      1379904.79      6832060.79
      1380134.49      6831853.22
#Sta/Elev= 30
  4819.5 2192.04  4847.3 2191.48  4853.8 2192.11  4868.2 2192.55  4876.9 2191.55
  4897.8 2190.22  4954.5  2189.2  4975.9 2189.29  5007.3 2188.84  5007.6 2188.34
  5011.1 2188.34  5011.3 2188.84  5016.1  2189.2  5023.5 2189.03  5044.5  2189.5
  5080.3 2189.67  5094.5  2190.3  5122.2 2190.66  5129.6 2191.48  5143.8 2192.33
    5158 2191.17  5172.2 2191.38    5179 2191.84  5193.2 2191.72  5221.6 2192.05
  5249.9 2193.36  5270.9 2195.35  5278.3 2194.57  5285.1 2194.33  5309.6 2194.69
#Mann= 3 ,-1 , 0
  4819.5     .07       0  5007.3     .07       0  5011.3     .07       0
Bank Sta=5007.3,5011.3
XS Rating Curve= 0 ,0
Exp/Cntr=0.3,0.1

Type RM Length L Ch R = 1 ,704     ,99,99,99
BEGIN DESCRIPTION:
Salt Branch Trib1 4140
END DESCRIPTION:
XS GIS Cut Line= 3
      1379742.02      6832109.39      1379955.07      6832215.25
      1380330.06       6831877.3
#Sta/Elev= 30
  4762.1 2192.27  4766.2 2192.27  4776.6 2190.72  4798.9 2189.92  4854.6 2188.92
  4860.2    2189  4865.9 2189.74  4888.3  2187.8  4995.5 2186.78  4995.7 2186.28
  4999.2 2186.28  4999.5 2186.78  5054.3 2187.63    5076 2188.55  5090.2 2189.64
  5104.4 2188.61  5188.9 2190.53  5210.5  2192.1  5224.7 2191.16  5281.5 2192.35
  5295.7 2192.95  5323.4 2195.23  5330.8 2194.36  5387.6 2194.99  5401.8 2196.01
  5408.6 2195.61    5437 2196.66  5457.9 2198.55  5486.3 2198.17  5504.8 2198.98
#Mann= 3 ,-1 , 0
  4762.1     .07       0  4995.5     .07       0  4999.5     .07       0
Bank Sta=4995.5,4999.5
XS Rating Curve= 0 ,0
Exp/Cntr=0.3,0.1

Type RM Length L Ch R = 1 ,605     ,185,185,185
BEGIN DESCRIPTION:
Salt Branch Trib1 4185
END DESCRIPTION:
XS GIS Cut Line= 3
      1379815.54      6832237.33      1379975.11      6832307.96
       1380241.5      6832114.72
#Sta/Elev= 30
  4825.5 2189.09  4840.4 2188.82  4846.8 2187.98  4857.7 2187.58  4879.6  2187.3
  4892.5 2186.88  4910.3 2186.98    4939 2186.56  4985.6 2186.35  4989.1 2186.14
  4989.3 2185.64  4992.8 2185.64  4993.1 2186.14  5049.3 2186.61  5057.5 2186.37
  5063.7 2186.71  5072.2 2186.56  5107.8 2187.07  5122.4 2187.47  5135.8 2188.13
  5149.5 2189.69  5164.2 2188.73  5235.3 2190.19  5264.7 2192.42  5279.4  2191.6
  5294.1 2191.53  5300.3 2191.86  5314.9 2192.02  5321.1 2192.51  5329.1  2192.5
#Mann= 3 ,-1 , 0
  4825.5     .07       0  4989.1     .07       0  4993.1     .07       0
Bank Sta=4989.1,4993.1
XS Rating Curve= 0 ,0
Exp/Cntr=0.3,0.1

Type RM Length L Ch R = 1 ,420     ,209,209,209
BEGIN DESCRIPTION:
Salt Branch Trib1 4141
END DESCRIPTION:
XS GIS Cut Line= 3
      1379815.88       6832343.8      1380038.33      6832471.51
      1380450.17      6832143.18
#Sta/Elev= 30
  4743.5 2189.45    4754 2189.16  4760.9 2187.98    4863 2185.86  4884.6 2187.07
  4900.4 2185.08  4925.7 2184.41  4925.9 2183.91  4929.7 2184.41  5043.1 2184.77
  5085.3 2185.81  5099.2 2186.88  5121.6 2185.86  5163.2 2186.93  5185.6 2187.69
  5206.5 2189.34  5227.3 2189.01  5256.1 2189.71  5291.3 2192.04  5334.6 2192.04
  5355.4 2193.06  5377.8  2195.6  5392.2 2194.44  5419.4 2195.01  5448.3 2196.45
  5462.7 2198.54  5477.1  2197.9  5497.9  2198.2  5520.1 2200.03  5526.7 2201.71
#Mann= 3 ,-1 , 0
  4743.5     .07       0  4925.7     .07       0  4929.7     .07       0
Bank Sta=4925.7,4929.7
XS Rating Curve= 0 ,0
Exp/Cntr=0.3,0.1

Type RM Length L Ch R = 1 ,211     ,93,93,93
BEGIN DESCRIPTION:
Salt Branch Trib1 4142
END DESCRIPTION:
XS GIS Cut Line= 3
      1379844.08      6832458.84      1379987.81      6832654.52
      1380458.17      6832463.15
#Sta/Elev= 30
  4757.2 2187.54  4821.1 2185.99    4843 2186.89  4885.9 2184.23  4915.2 2183.68
  4942.3 2184.76  4950.7 2184.35  4979.5 2182.49  4986.3 2180.38  4997.1 2175.57
  4997.3 2175.07  5001.1 2175.57  5032.7  2176.4  5040.1 2177.34  5056.7 2183.32
  5062.1 2181.88  5072.5 2183.15  5115.7 2183.17  5139.7 2184.35  5163.8  2183.8
  5241.4 2184.77  5270.8 2186.68  5294.9 2185.87  5331.6 2187.15  5353.8  2189.3
  5385.6 2188.91    5418 2189.88  5439.6 2192.31    5472 2191.92  5507.8 2192.89
#Mann= 3 ,-1 , 0
  4757.2     .07       0  4997.1     .07       0  5001.1     .07       0
Bank Sta=4997.1,5001.1
XS Rating Curve= 0 ,0
Exp/Cntr=0.3,0.1

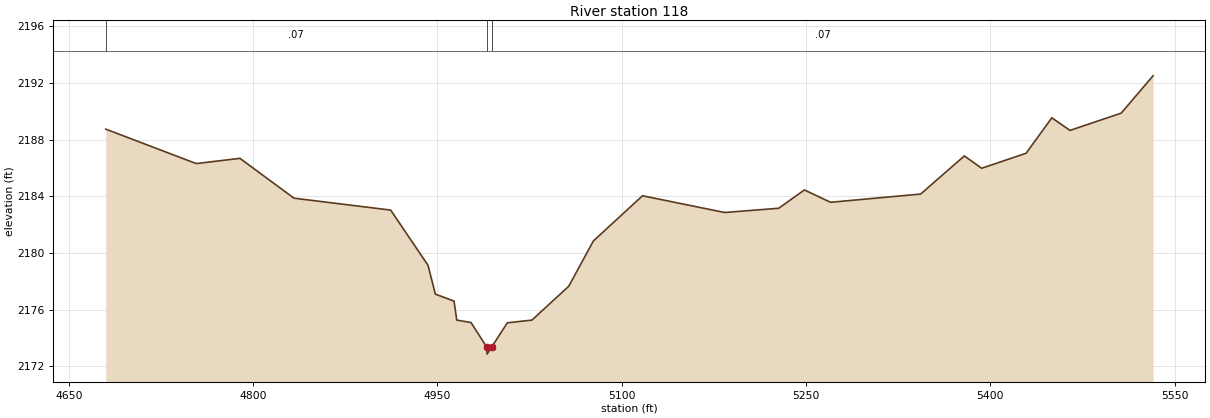
Type RM Length L Ch R = 1 ,118     ,0,0,0
BEGIN DESCRIPTION:
Salt Branch Trib1 4475
END DESCRIPTION:
XS GIS Cut Line= 5
      1379776.12      6832475.97      1379930.17      6832716.82
      1379958.15      6832736.32      1380104.87      6832740.69
      1380418.44      6832516.09
#Sta/Elev= 30
    4680 2188.74  4753.6 2186.31  4789.2 2186.68  4833.2 2183.87  4911.9 2183.03
  4942.3 2179.14  4948.3  2177.1  4963.5 2176.61  4965.7 2175.27  4977.3  2175.1
  4990.1 2173.37  4990.4 2172.87  4994.1 2173.37  5006.9 2175.08  5026.9 2175.27
  5056.9 2177.66  5076.9 2180.85  5116.9 2184.04  5183.8 2182.86  5227.8 2183.16
  5248.7 2184.45    5270 2183.58  5343.3 2184.16  5378.9 2186.85    5393 2185.98
  5429.2 2187.04  5450.1 2189.54  5464.9 2188.65  5506.6 2189.87  5532.5  2192.5
#Mann= 3 ,-1 , 0
    4680     .07       0  4990.1     .07       0  4994.1     .07       0
Bank Sta=4990.1,4994.1
XS Rating Curve= 0 ,0
Exp/Cntr=0.3,0.1

Chan Stop Cuts=-1
Use User Specified Reach Order=0
Composite Channel Slope=5