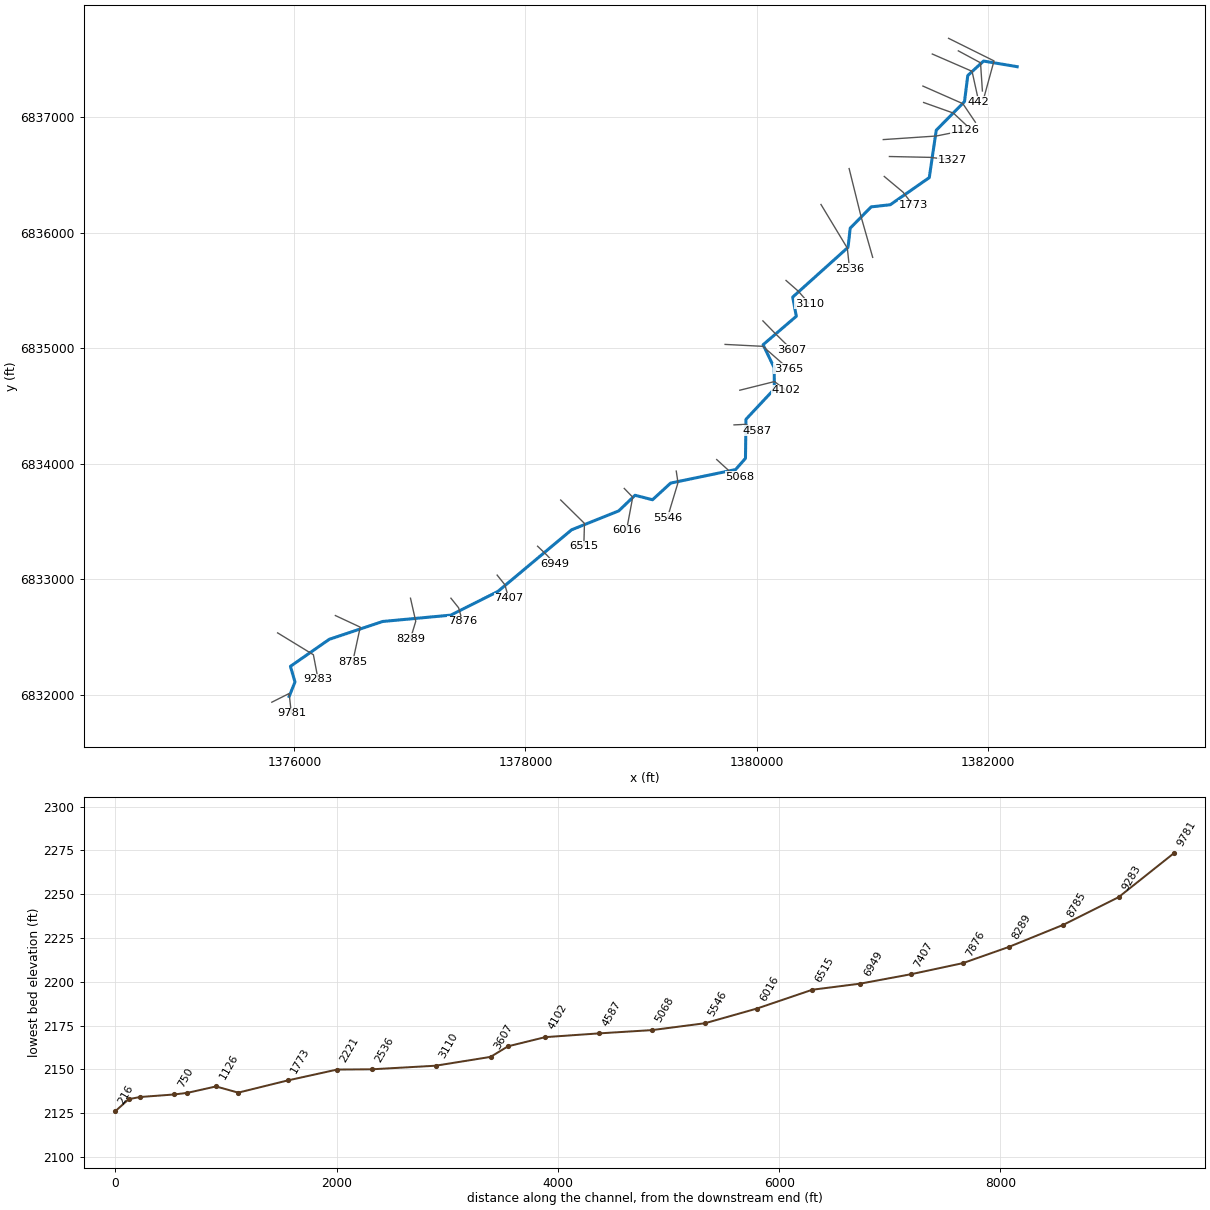
--- Salt Branch Trib2.prj (project) ---

Proj Title=Salt Branch Trib2 Base Level Engineering
Current Plan=p01
Default Exp/Contr=0.3,0.1
English Units
Geom File=g01
Flow File=f01
Plan File=p01
Y Axis Title=Elevation
X Axis Title(PF)=Main Channel Distance
X Axis Title(XS)=Station
BEGIN DESCRIPTION:
Salt Branch Trib2
END DESCRIPTION:
DSS Export Rating Curves= 0
DSS Export Rating Curve Sorted= 0
DSS Export Volume Flow Curves= 0
DXF OffsetX= 0
DXF OffsetY= 0
DXF ScaleX= 1
DXF ScaleY= 10

--- Salt Branch Trib2.p01 (plan) ---

Plan Title=Multiple Run
Short Identifier=Multiple
Geom File=g01
Flow File=f01
Subcritical Flow
K Sum by GR= 0
Std Step Tol= 0.01
Critical Tol= 0.01
Num of Std Step Trials= 20
Max Error Tol= 0.3
Flow Tol Ratio= 0.001
Split Flow NTrial= 30
Split Flow Tol= 0.02
Split Flow Ratio= 0.02
Log Output Level= 0
Friction Slope Method= 1
Unsteady Friction Slope Method= 2
Unsteady Bridges Friction Slope Method= 1
Parabolic Critical Depth
Global Vel Dist=  1 , 1 , 1
Global Log Level= 0
CheckData=True
Encroach Param= -1, 0, 0, 0
BEGIN DESCRIPTION:
Multiple Run
END DESCRIPTION:

--- Salt Branch Trib2.f01 (steady flow) ---

Flow Title=Multiple
Number of Profiles=7
Profile Names=10-year,25-year,50-year,1pct_min,100-year,1pct_plu,500-year
River Rch & RM= Salt Branch Trib,Reach-1,9781
     187     260     321     197     393     784     597
Boundary for River Rch & Prof#=Salt Branch Trib,Reach-1,1
Up Type=0
Dn Type=3
Dn Slope=0.005
Boundary for River Rch & Prof#=Salt Branch Trib,Reach-1,2
Up Type=0
Dn Type=3
Dn Slope=0.005
Boundary for River Rch & Prof#=Salt Branch Trib,Reach-1,3
Up Type=0
Dn Type=3
Dn Slope=0.005
Boundary for River Rch & Prof#=Salt Branch Trib,Reach-1,4
Up Type=0
Dn Type=3
Dn Slope=0.005
Boundary for River Rch & Prof#=Salt Branch Trib,Reach-1,5
Up Type=0
Dn Type=3
Dn Slope=0.005
Boundary for River Rch & Prof#=Salt Branch Trib,Reach-1,6
Up Type=0
Dn Type=3
Dn Slope=0.005
Boundary for River Rch & Prof#=Salt Branch Trib,Reach-1,7
Up Type=0
Dn Type=3
Dn Slope=0.005

--- Salt Branch Trib2.g01 (geometry) ---

Geom Title=Existing Conditions

River Reach=Salt Branch Trib,Reach-1
Reach XY= 30
      1375955.00      6831988.00      1376005.43      6832112.99
      1375965.97      6832248.38      1376302.55      6832482.53
      1376764.66      6832636.62      1377353.53      6832691.56
      1377761.05      6832896.16      1378398.94      6833429.86
      1378807.30      6833593.83      1378948.26      6833728.87
      1379099.52      6833690.08      1379256.50      6833834.39
      1379818.35      6833951.36      1379903.96      6834048.43
      1379908.54      6834386.54      1380153.81      6834648.48
      1380152.76      6834832.07      1380056.61      6835031.97
      1380343.90      6835277.94      1380312.76      6835444.17
      1380791.63      6835874.68      1380810.47      6836040.45
      1380991.68      6836224.63      1381157.45      6836243.47
      1381494.66      6836477.88      1381555.00      6836888.00
      1381799.54      6837135.55      1381827.86      6837361.53
      1381964.59      6837486.80      1382255.00      6837438.00

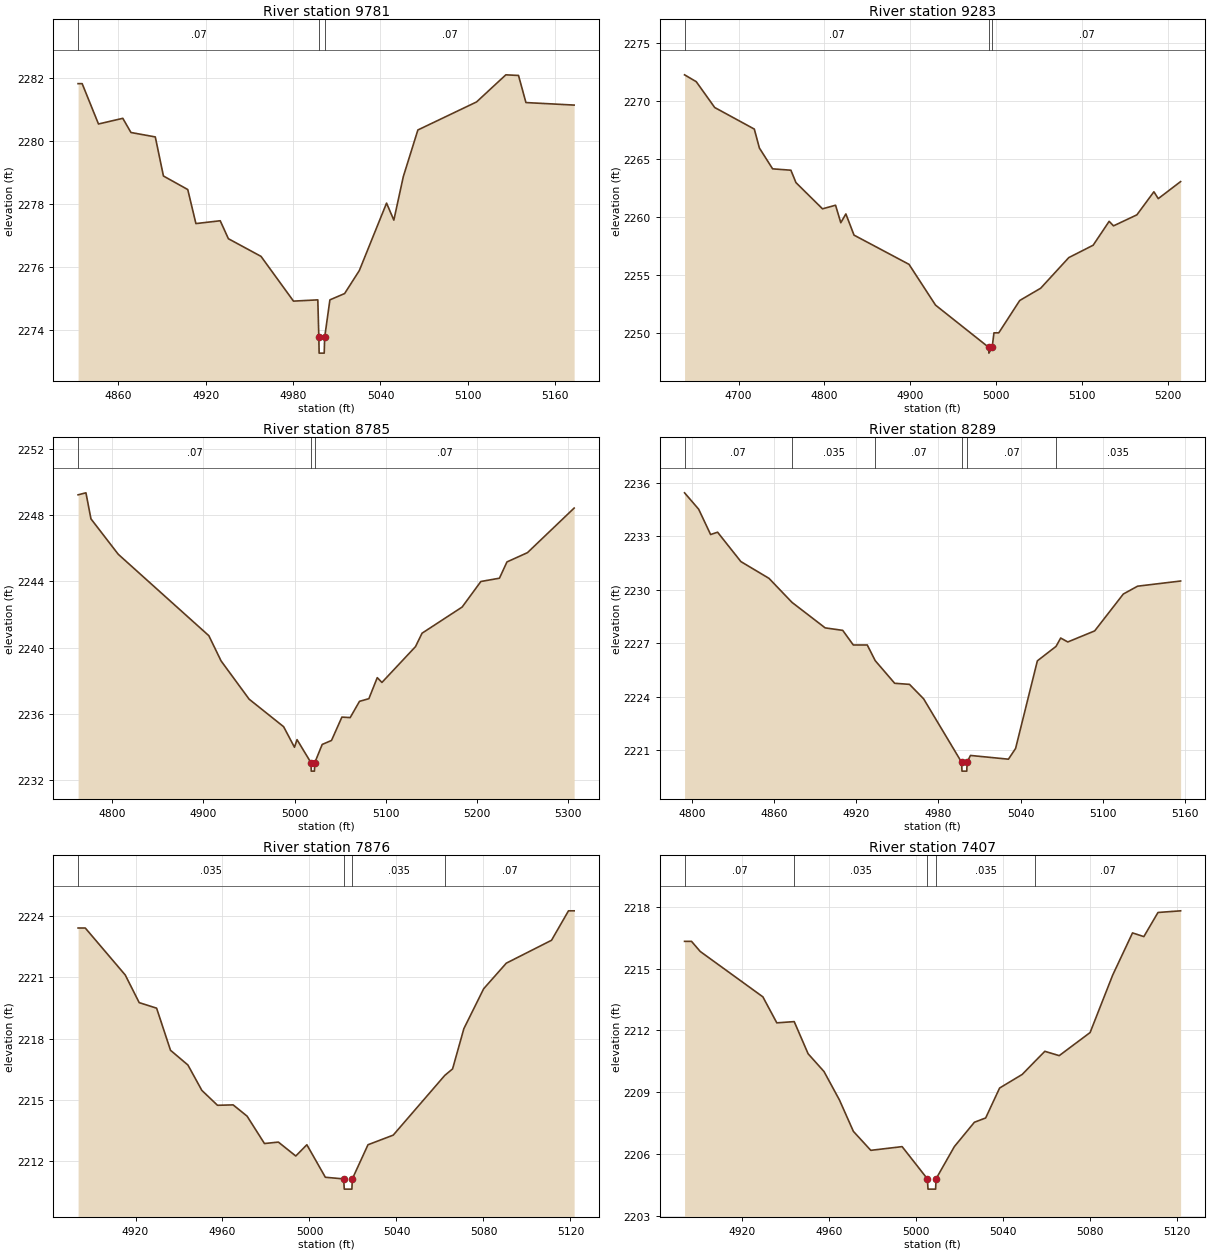
Type RM Length L Ch R = 1,9781,498,498,498
BEGIN DESCRIPTION:
Salt Branch Trib2 19.0
END DESCRIPTION:
XS GIS Cut Line= 3
      1375805.01      6831938.00      1375954.73      6832013.31
      1375973.79      6831841.36
#Sta/Elev= 30
  4832.4 2281.83  4835.2 2281.83  4846.4 2280.55  4863.1 2280.73  4868.7 2280.28
  4885.4 2280.14  4891.0 2278.90  4907.7 2278.47  4913.3 2277.39  4930.0 2277.48
  4935.6 2276.91  4958.0 2276.35  4980.3 2274.93  4997.0 2274.97  4997.7 2273.78
  4997.9 2273.28  5001.4 2273.28  5001.7 2273.78  5005.3 2274.97  5015.4 2275.17
  5025.5 2275.90  5044.2 2278.04  5049.2 2277.50  5055.7 2278.88  5065.7 2280.36
  5106.0 2281.25  5126.1 2282.11  5134.8 2282.09  5139.9 2281.23  5173.0 2281.15
#Mann=3,-1,0
  4832.4    0.07       0  4997.7    0.07       0  5001.7    0.07       0
Bank Sta=4997.7,5001.7
Exp/Cntr=0.3,0.1

Type RM Length L Ch R = 1,9283,498,498,498
BEGIN DESCRIPTION:
Salt Branch Trib2 18.0
END DESCRIPTION:
XS GIS Cut Line= 3
      1375855.02      6832537.99      1376164.68      6832348.77
      1376205.00      6832137.99
#Sta/Elev= 30
  4637.1 2272.29  4650.7 2271.70  4672.2 2269.47  4718.3 2267.61  4724.2 2265.98
  4739.6 2264.18  4760.9 2264.06  4766.8 2262.99  4797.7 2260.73  4812.9 2261.04
  4819.0 2259.53  4824.9 2260.29  4834.4 2258.46  4898.4 2255.94  4929.3 2252.42
  4991.2 2248.78  4991.4 2248.28  4995.2 2248.78  4997.3 2250.03  5002.9 2250.03
  5027.3 2252.82  5051.7 2253.88  5084.4 2256.52  5112.8 2257.59  5131.4 2259.65
  5136.5 2259.26  5163.7 2260.21  5183.5 2262.20  5188.6 2261.61  5214.6 2263.08
#Mann=3,-1,0
  4637.1    0.07       0  4991.2    0.07       0  4995.2    0.07       0
Bank Sta=4991.2,4995.2
Exp/Cntr=0.3,0.1

Type RM Length L Ch R = 1,8785,496,496,496
BEGIN DESCRIPTION:
Salt Branch Trib2 17.0
END DESCRIPTION:
XS GIS Cut Line= 3
      1376355.04      6832687.98      1376570.17      6832587.60
      1376505.00      6832288.00
#Sta/Elev= 30
  4762.6 2249.22  4771.2 2249.34  4776.7 2247.77  4806.7 2245.63  4906.0 2240.72
  4919.4 2239.20  4950.2 2236.89  4988.0 2235.23  4999.9 2233.99  5002.7 2234.45
  5018.1 2233.05  5018.3 2232.55  5021.8 2232.55  5022.1 2233.05  5030.3 2234.16
  5040.5 2234.40  5051.9 2235.81  5061.0 2235.78  5071.2 2236.76  5081.5 2236.92
  5090.7 2238.19  5095.8 2237.90  5132.6 2240.06  5139.8 2240.87  5183.8 2242.45
  5204.3 2243.99  5224.7 2244.19  5232.9 2245.17  5255.4 2245.73  5306.6 2248.42
#Mann=3,-1,0
  4762.6    0.07       0  5018.1    0.07       0  5022.1    0.07       0
Bank Sta=5018.1,5022.1
Exp/Cntr=0.3,0.1

Type RM Length L Ch R = 1,8289,413,413,413
BEGIN DESCRIPTION:
Salt Branch Trib2 16.0
END DESCRIPTION:
XS GIS Cut Line= 3
      1377004.99      6832838.03      1377050.48      6832637.94
      1377005.00      6832487.98
#Sta/Elev= 30
  4794.8 2235.45  4805.1 2234.53  4813.8 2233.11  4818.9 2233.24  4835.9 2231.59
  4856.4 2230.65  4873.2 2229.30  4897.4 2227.87  4910.2 2227.73  4917.9 2226.91
  4928.1 2226.91  4933.9 2226.03  4948.1 2224.76  4958.9 2224.70  4969.2 2223.89
  4996.9 2220.33  4997.2 2219.83  5000.7 2219.83  5000.9 2220.33  5003.4 2220.71
  5031.1 2220.50  5036.3 2221.10  5052.2 2226.02  5065.8 2226.83  5069.2 2227.30
  5074.4 2227.08  5094.0 2227.70  5114.9 2229.77  5125.3 2230.21  5156.7 2230.50
#Mann=6,-1,0
  4794.8    0.07       0  4873.2   0.035       0  4933.9    0.07       0
  4996.9    0.07       0  5000.9    0.07       0  5065.8   0.035       0
Bank Sta=4996.9,5000.9
Exp/Cntr=0.3,0.1

Type RM Length L Ch R = 1,7876,469,469,469
BEGIN DESCRIPTION:
Salt Branch Trib2 15.0
END DESCRIPTION:
XS GIS Cut Line= 3
      1377354.97      6832838.04      1377421.52      6832755.02
      1377455.00      6832638.02
#Sta/Elev= 30
  4893.6 2223.41  4896.9 2223.41  4915.3 2221.11  4921.7 2219.76  4929.7 2219.49
  4936.1 2217.43  4944.1 2216.71  4950.5 2215.47  4957.7 2214.74  4964.9 2214.76
  4971.3 2214.21  4979.3 2212.87  4985.7 2212.94  4993.7 2212.26  4998.8 2212.81
  5007.3 2211.22  5015.7 2211.14  5016.0 2210.64  5019.5 2210.64  5019.7 2211.14
  5026.9 2212.81  5038.5 2213.28  5062.2 2216.20  5065.8 2216.52  5071.0 2218.49
  5080.1 2220.44  5090.5 2221.69  5111.3 2222.81  5119.1 2224.25  5121.7 2224.25
#Mann=4,-1,0
  4893.6   0.035       0  5015.7   0.035       0  5019.7   0.035       0
  5062.2    0.07       0
Bank Sta=5015.7,5019.7
Exp/Cntr=0.3,0.1

Type RM Length L Ch R = 1,7407,458,458,458
BEGIN DESCRIPTION:
Salt Branch Trib2 14.0
END DESCRIPTION:
XS GIS Cut Line= 3
      1377755.01      6833037.98      1377821.55      6832954.95
      1377854.99      6832838.04
#Sta/Elev= 30
  4893.6 2216.32  4896.8 2216.32  4900.8 2215.83  4929.6 2213.63  4936.0 2212.37
  4944.0 2212.43  4950.4 2210.87  4957.7 2210.01  4964.8 2208.63  4971.2 2207.11
  4979.2 2206.19  4993.6 2206.37  5005.2 2204.81  5005.5 2204.31  5009.0 2204.31
  5009.2 2204.81  5017.6 2206.37  5026.8 2207.55  5032.0 2207.76  5038.4 2209.21
  5048.8 2209.87  5054.9 2210.53  5059.2 2210.99  5065.8 2210.78  5080.0 2211.90
  5090.4 2214.69  5099.5 2216.73  5104.7 2216.55  5111.2 2217.72  5121.6 2217.80
#Mann=5,-1,0
  4893.6    0.07       0  4944.0   0.035       0  5005.2   0.035       0
  5009.2   0.035       0  5054.9    0.07       0
Bank Sta=5005.2,5009.2
Exp/Cntr=0.3,0.1

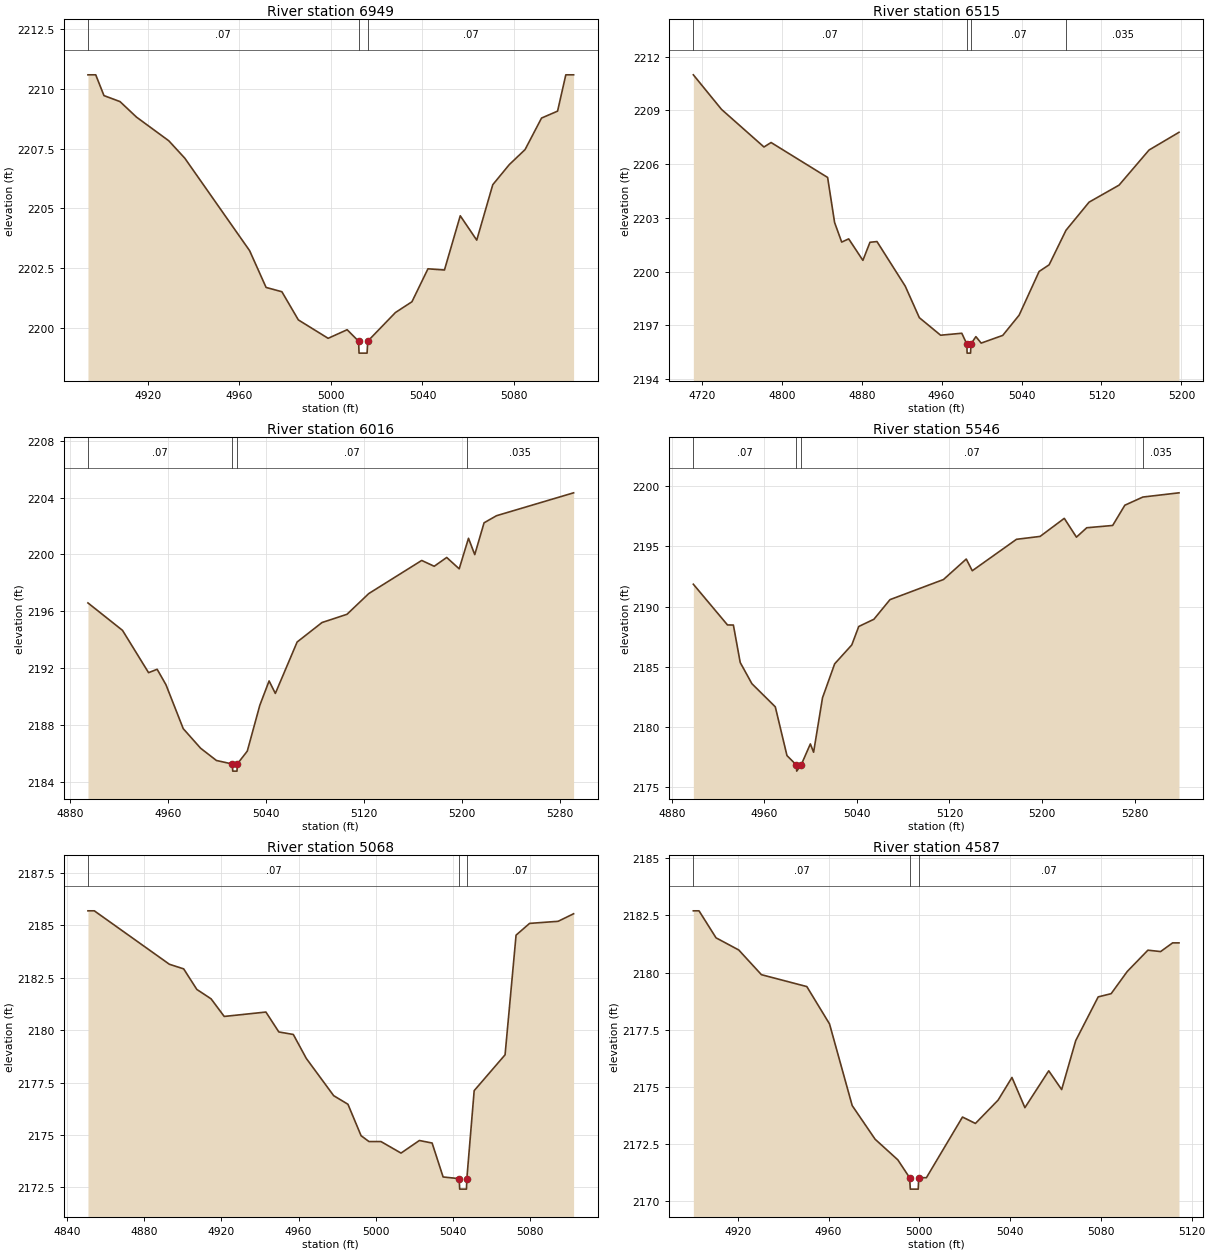
Type RM Length L Ch R = 1,6949,434,434,434
BEGIN DESCRIPTION:
Salt Branch Trib2 13.0
END DESCRIPTION:
XS GIS Cut Line= 3
      1378105.03      6833287.97      1378181.69      6833214.62
      1378254.97      6833138.03
#Sta/Elev= 30
  4893.9 2210.59  4897.3 2210.59  4900.9 2209.72  4907.9 2209.47  4915.1 2208.82
  4929.2 2207.83  4936.2 2207.10  4964.5 2203.23  4971.7 2201.69  4978.6 2201.51
  4985.8 2200.33  4998.8 2199.56  5007.1 2199.92  5012.1 2199.44  5012.3 2198.94
  5015.8 2198.94  5016.1 2199.44  5028.2 2200.64  5035.4 2201.09  5042.4 2202.47
  5049.6 2202.42  5056.5 2204.69  5063.7 2203.67  5070.7 2205.99  5077.9 2206.83
  5084.8 2207.46  5092.0 2208.78  5099.0 2209.07  5102.6 2210.59  5106.0 2210.59
#Mann=3,-1,0
  4893.9    0.07       0  5012.1    0.07       0  5016.1    0.07       0
Bank Sta=5012.1,5016.1
Exp/Cntr=0.3,0.1

Type RM Length L Ch R = 1,6515,499,499,499
BEGIN DESCRIPTION:
Salt Branch Trib2 12.0
END DESCRIPTION:
XS GIS Cut Line= 3
      1378305.01      6833687.99      1378510.56      6833485.56
      1378505.00      6833288.03
#Sta/Elev= 30
  4711.5 2210.99  4739.7 2209.06  4782.2 2206.96  4789.3 2207.21  4845.9 2205.26
  4852.9 2202.74  4860.0 2201.65  4867.0 2201.83  4881.2 2200.63  4888.3 2201.64
  4895.3 2201.68  4923.6 2199.19  4937.7 2197.43  4959.0 2196.45  4980.2 2196.56
  4985.3 2195.95  4985.5 2195.45  4989.0 2195.45  4989.3 2195.95  4994.3 2196.37
  4999.6 2196.01  5021.2 2196.44  5037.6 2197.57  5057.6 2200.01  5067.6 2200.38
  5084.5 2202.31  5107.6 2203.88  5137.6 2204.83  5167.6 2206.79  5197.6 2207.78
#Mann=4,-1,0
  4711.5    0.07       0  4985.3    0.07       0  4989.3    0.07       0
  5084.5   0.035       0
Bank Sta=4985.3,4989.3
Exp/Cntr=0.3,0.1

Type RM Length L Ch R = 1,6016,470,470,470
BEGIN DESCRIPTION:
Salt Branch Trib2 11.0
END DESCRIPTION:
XS GIS Cut Line= 4
      1378855.00      6833788.00      1378928.31      6833712.28
      1378905.00      6833588.00      1378874.64      6833426.17
#Sta/Elev= 30
  4894.6 2196.58  4922.8 2194.65  4944.1 2191.67  4951.1 2191.91  4958.3 2190.82
  4972.4 2187.73  4986.6 2186.35  4999.5 2185.49  5012.5 2185.24  5012.8 2184.74
  5016.3 2184.74  5016.5 2185.24  5024.7 2186.15  5034.9 2189.37  5042.5 2191.09
  5047.6 2190.21  5065.4 2193.83  5085.7 2195.20  5106.1 2195.78  5123.9 2197.24
  5167.1 2199.57  5177.3 2199.16  5187.5 2199.78  5197.7 2198.98  5203.7 2200.68
  5205.3 2201.13  5210.4 2199.98  5218.0 2202.22  5228.2 2202.72  5291.1 2204.33
#Mann=4,-1,0
  4894.6    0.07       0  5012.5    0.07       0  5016.5    0.07       0
  5203.7   0.035       0
Bank Sta=5012.5,5016.5
Exp/Cntr=0.3,0.1

Type RM Length L Ch R = 1,5546,478,478,478
BEGIN DESCRIPTION:
Salt Branch Trib2 10.0
END DESCRIPTION:
XS GIS Cut Line= 4
      1379304.99      6833938.04      1379320.06      6833837.87
      1379305.00      6833788.00      1379228.06      6833533.15
#Sta/Elev= 30
  4898.7 2191.86  4928.2 2188.48  4933.3 2188.47  4939.2 2185.36  4949.3 2183.60
  4969.5 2181.68  4979.6 2177.63  4987.8 2176.84  4988.0 2176.34  4991.8 2176.84
  4999.8 2178.60  5002.6 2177.91  5010.3 2182.43  5020.8 2185.25  5035.6 2186.82
  5041.6 2188.35  5054.7 2188.95  5068.6 2190.58  5114.8 2192.25  5134.5 2193.95
  5139.7 2192.98  5177.9 2195.59  5198.3 2195.83  5219.2 2197.33  5229.7 2195.77
  5238.6 2196.55  5261.0 2196.74  5271.5 2198.42  5287.1 2199.10  5318.3 2199.45
#Mann=4,-1,0
  4898.7    0.07       0  4987.8    0.07       0  4991.8    0.07       0
  5287.1   0.035       0
Bank Sta=4987.8,4991.8
Exp/Cntr=0.3,0.1

Type RM Length L Ch R = 1,5068,481,481,481
BEGIN DESCRIPTION:
Salt Branch Trib2 9.0
END DESCRIPTION:
XS GIS Cut Line= 3
      1379655.04      6834037.97      1379765.21      6833937.50
      1379854.97      6833888.02
#Sta/Elev= 30
  4850.9 2185.70  4854.2 2185.70  4893.1 2183.15  4900.5 2182.93  4907.3 2181.95
  4914.7 2181.50  4921.5 2180.66  4943.1 2180.87  4949.8 2179.92  4957.3 2179.80
  4964.0 2178.66  4978.2 2176.88  4985.6 2176.47  4992.4 2174.97  4996.5 2174.69
  5002.7 2174.69  5013.1 2174.14  5022.6 2174.74  5029.2 2174.62  5034.9 2173.00
  5043.2 2172.92  5043.5 2172.42  5047.0 2172.42  5047.2 2172.92  5051.0 2177.12
  5067.0 2178.83  5072.7 2184.54  5079.7 2185.10  5094.5 2185.20  5102.5 2185.56
#Mann=3,-1,0
  4850.9    0.07       0  5043.2    0.07       0  5047.2    0.07       0
Bank Sta=5043.2,5047.2
Exp/Cntr=0.3,0.1

Type RM Length L Ch R = 1,4587,485,485,485
BEGIN DESCRIPTION:
Salt Branch Trib2 8.0
END DESCRIPTION:
XS GIS Cut Line= 3
      1379805.04      6834338.00      1379904.52      6834342.74
      1380004.98      6834288.01
#Sta/Elev= 30
  4900.4 2182.70  4902.9 2182.70  4910.4 2181.52  4920.4 2180.99  4930.4 2179.91
  4950.4 2179.39  4960.4 2177.76  4970.4 2174.19  4980.5 2172.72  4990.5 2171.82
  4995.7 2171.04  4996.0 2170.54  4999.5 2170.54  4999.7 2171.04  5003.1 2171.04
  5019.0 2173.69  5024.7 2173.41  5034.7 2174.43  5040.8 2175.42  5046.5 2174.10
  5057.0 2175.71  5062.7 2174.89  5068.9 2177.03  5078.8 2178.94  5084.5 2179.08
  5091.6 2180.05  5100.7 2180.98  5106.3 2180.92  5111.6 2181.30  5114.4 2181.30
#Mann=3,-1,0
  4900.4    0.07       0  4995.7    0.07       0  4999.7    0.07       0
Bank Sta=4995.7,4999.7
Exp/Cntr=0.3,0.1

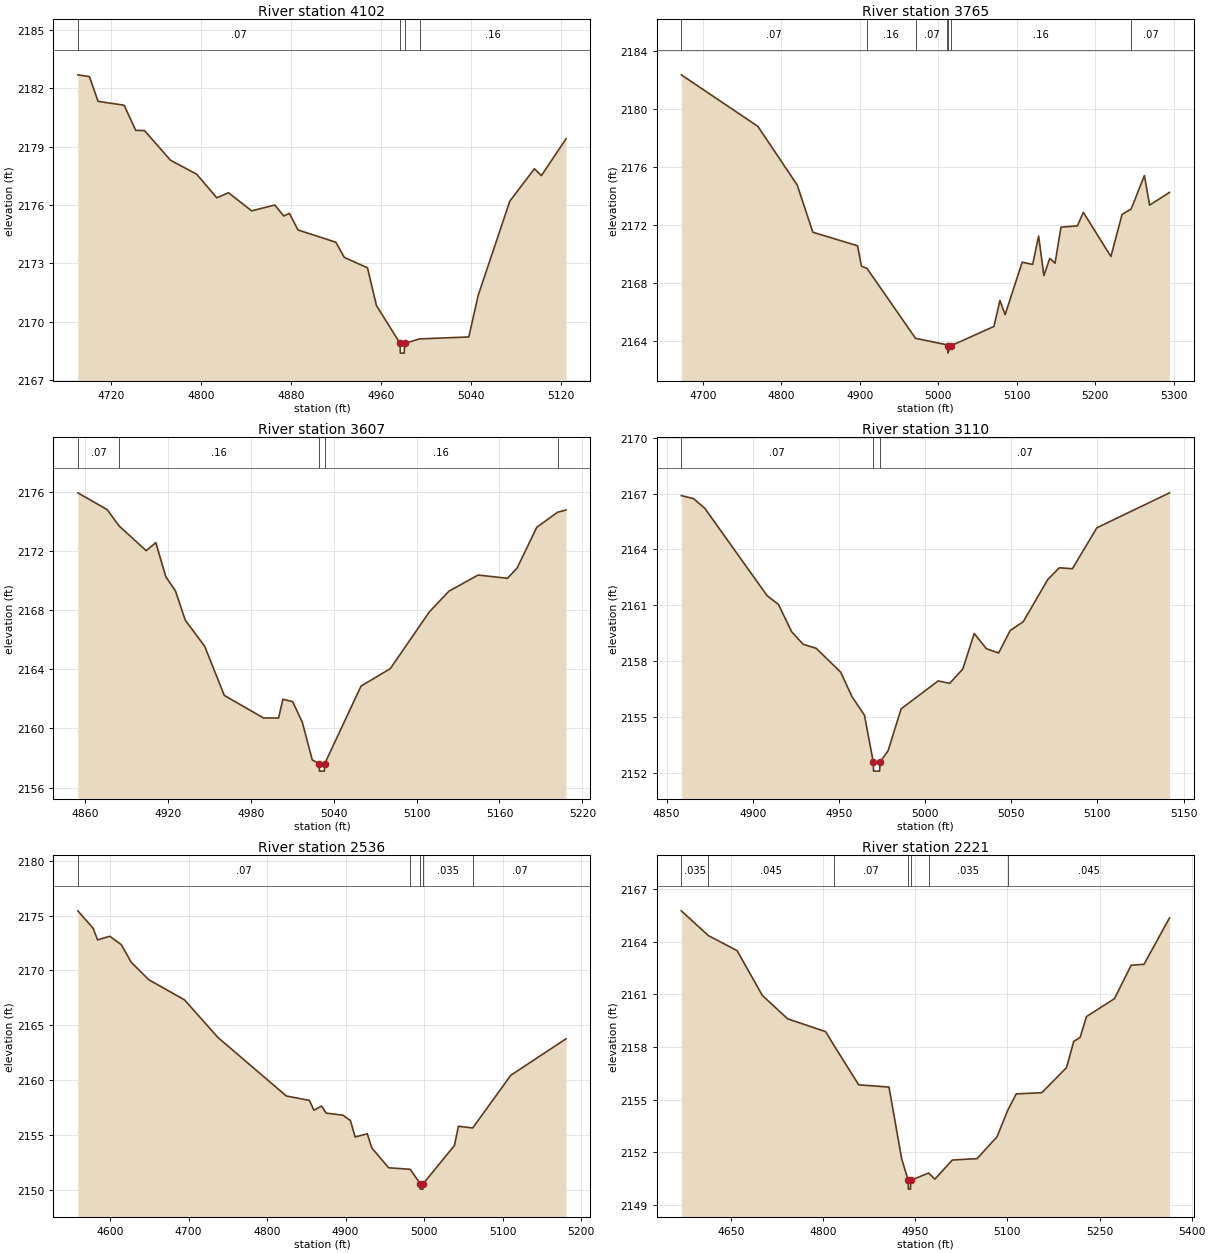
Type RM Length L Ch R = 1,4102,337,337,337
BEGIN DESCRIPTION:
Salt Branch Trib2 7.0
END DESCRIPTION:
XS GIS Cut Line= 3
      1379855.03      6834638.01      1380155.23      6834712.93
      1380255.02      6834637.98
#Sta/Elev= 30
  4690.6 2182.68  4700.9 2182.59  4708.6 2181.32  4731.8 2181.12  4742.1 2179.83
  4749.9 2179.82  4773.0 2178.30  4796.3 2177.58  4814.2 2176.37  4824.6 2176.63
  4845.2 2175.70  4865.8 2176.00  4873.7 2175.44  4878.8 2175.57  4886.4 2174.72
  4920.1 2174.09  4927.6 2173.31  4948.2 2172.78  4956.2 2170.84  4977.2 2168.90
  4977.4 2168.40  4980.9 2168.40  4981.2 2168.90  4994.6 2169.13  5038.3 2169.23
  5046.7 2171.37  5074.8 2176.20  5096.7 2177.86  5102.9 2177.51  5124.8 2179.40
#Mann=4,-1,0
  4690.6    0.07       0  4977.2    0.07       0  4981.2    0.07       0
  4994.6    0.16       0
Bank Sta=4977.2,4981.2
Exp/Cntr=0.3,0.1

Type RM Length L Ch R = 1,3765,158,158,158
BEGIN DESCRIPTION:
Salt Branch Trib2 4093
END DESCRIPTION:
XS GIS Cut Line= 3
      1379727.61      6835034.48      1380054.59      6835017.87
      1380276.13      6834823.68
#Sta/Elev= 30
  4672.6 2182.34  4770.1 2178.79  4820.2 2174.75  4840.2 2171.49  4897.1 2170.56
  4902.1 2169.15  4909.0 2169.01  4971.0 2164.18  5011.2 2163.73  5011.9 2163.66
  5012.2 2163.16  5015.9 2163.66  5070.9 2165.00  5078.5 2166.79  5085.1 2165.81
  5106.9 2169.43  5120.2 2169.27  5127.8 2171.23  5134.5 2168.50  5142.0 2169.69
  5148.7 2169.36  5156.3 2171.84  5177.2 2171.93  5184.8 2172.86  5219.9 2169.82
  5234.1 2172.72  5245.7 2173.09  5262.6 2175.40  5269.2 2173.36  5294.6 2174.24
#Mann=7,-1,0
  4672.6    0.07       0  4909.0    0.16       0  4971.0    0.07       0
  5011.2    0.16       0  5011.9    0.07       0  5015.9    0.16       0
  5245.7    0.07       0
Bank Sta=5011.9,5015.9
Exp/Cntr=0.3,0.1

Type RM Length L Ch R = 1,3607,497,497,497
BEGIN DESCRIPTION:
Salt Branch Trib2 6.0
END DESCRIPTION:
XS GIS Cut Line= 3
      1380055.00      6835238.00      1380156.63      6835134.03
      1380305.02      6834987.98
#Sta/Elev= 30
  4854.6 2175.93  4875.8 2174.80  4884.5 2173.69  4904.1 2172.02  4911.1 2172.56
  4918.3 2170.26  4925.3 2169.30  4932.4 2167.32  4946.5 2165.55  4960.7 2162.23
  4989.0 2160.71  5000.0 2160.70  5003.1 2161.97  5010.2 2161.81  5017.2 2160.41
  5024.4 2157.87  5029.4 2157.61  5029.6 2157.11  5033.1 2157.11  5033.4 2157.61
  5059.7 2162.86  5080.9 2164.04  5109.2 2167.88  5123.4 2169.28  5144.5 2170.37
  5165.8 2170.15  5172.8 2170.85  5187.0 2173.60  5202.1 2174.62  5208.2 2174.77
#Mann=5,-1,0
  4854.6    0.07       0  4884.5    0.16       0  5029.4    0.07       0
  5033.4    0.16       0  5202.1    0.07       0
Bank Sta=5029.4,5033.4
Exp/Cntr=0.3,0.1

Type RM Length L Ch R = 1,3110,574,574,574
BEGIN DESCRIPTION:
Salt Branch Trib2 5.0
END DESCRIPTION:
XS GIS Cut Line= 3
      1380255.03      6835587.97      1380361.48      6835494.76
      1380454.98      6835388.02
#Sta/Elev= 30
  4858.5 2166.89  4865.6 2166.73  4872.2 2166.20  4908.3 2161.51  4914.9 2161.04
  4922.5 2159.58  4929.2 2158.90  4936.8 2158.68  4951.0 2157.40  4957.6 2156.08
  4964.8 2155.09  4969.9 2152.58  4970.1 2152.08  4973.6 2152.08  4973.9 2152.58
  4978.5 2153.17  4986.1 2155.43  5007.6 2156.93  5014.3 2156.80  5021.9 2157.57
  5028.5 2159.48  5035.6 2158.66  5042.7 2158.43  5049.4 2159.64  5057.0 2160.11
  5071.2 2162.38  5077.9 2163.01  5085.5 2162.96  5099.7 2165.16  5141.9 2167.04
#Mann=3,-1,0
  4858.5    0.07       0  4969.9    0.07       0  4973.9    0.07       0
Bank Sta=4969.9,4973.9
Exp/Cntr=0.3,0.1

Type RM Length L Ch R = 1,2536,315,315,315
BEGIN DESCRIPTION:
Salt Branch Trib2 4.0
END DESCRIPTION:
XS GIS Cut Line= 3
      1380557.53      6836245.41      1380785.39      6835867.84
      1380805.00      6835688.00
#Sta/Elev= 30
  4559.0 2175.44  4578.3 2173.87  4584.2 2172.79  4599.7 2173.12  4614.4 2172.35
  4626.9 2170.76  4649.4 2169.15  4694.8 2167.32  4737.5 2163.88  4824.6 2158.54
  4853.9 2158.14  4859.8 2157.24  4869.5 2157.62  4875.3 2156.98  4896.7 2156.79
  4906.3 2156.29  4912.2 2154.80  4927.7 2155.09  4933.5 2153.80  4954.9 2151.99
  4982.5 2151.85  4995.0 2150.54  4995.2 2150.04  4998.7 2150.04  4999.0 2150.54
  5038.8 2154.03  5043.8 2155.78  5062.0 2155.62  5110.5 2160.43  5180.9 2163.76
#Mann=5,-1,0
  4559.0    0.07       0  4982.5   0.035       0  4995.0   0.035       0
  4999.0   0.035       0  5062.0    0.07       0
Bank Sta=4995,4999
Exp/Cntr=0.3,0.1

Type RM Length L Ch R = 1,2221,448,448,448
BEGIN DESCRIPTION:
Salt Branch Trib2 3.0
END DESCRIPTION:
XS GIS Cut Line= 3
      1380801.14      6836556.12      1380904.98      6836138.02
      1381004.99      6835788.03
#Sta/Elev= 30
  4569.2 2165.76  4613.2 2164.35  4660.0 2163.49  4701.2 2160.93  4742.4 2159.60
  4804.2 2158.87  4817.1 2158.12  4857.9 2155.84  4907.3 2155.71  4927.9 2151.62
  4938.6 2150.39  4938.8 2149.89  4942.3 2149.89  4942.6 2150.39  4971.8 2150.81
  4981.9 2150.46  5010.4 2151.55  5050.7 2151.63  5083.2 2152.88  5100.5 2154.38
  5114.4 2155.32  5156.0 2155.39  5196.3 2156.82  5208.0 2158.31  5218.4 2158.54
  5228.8 2159.73  5274.3 2160.75  5301.6 2162.66  5322.4 2162.71  5364.0 2165.36
#Mann=7,-1,0
  4569.2   0.035       0  4613.2   0.045       0  4817.1    0.07       0
  4938.6   0.035       0  4942.6    0.07       0  4971.8   0.035       0
  5100.5   0.045       0
Bank Sta=4938.6,4942.6
Exp/Cntr=0.3,0.1

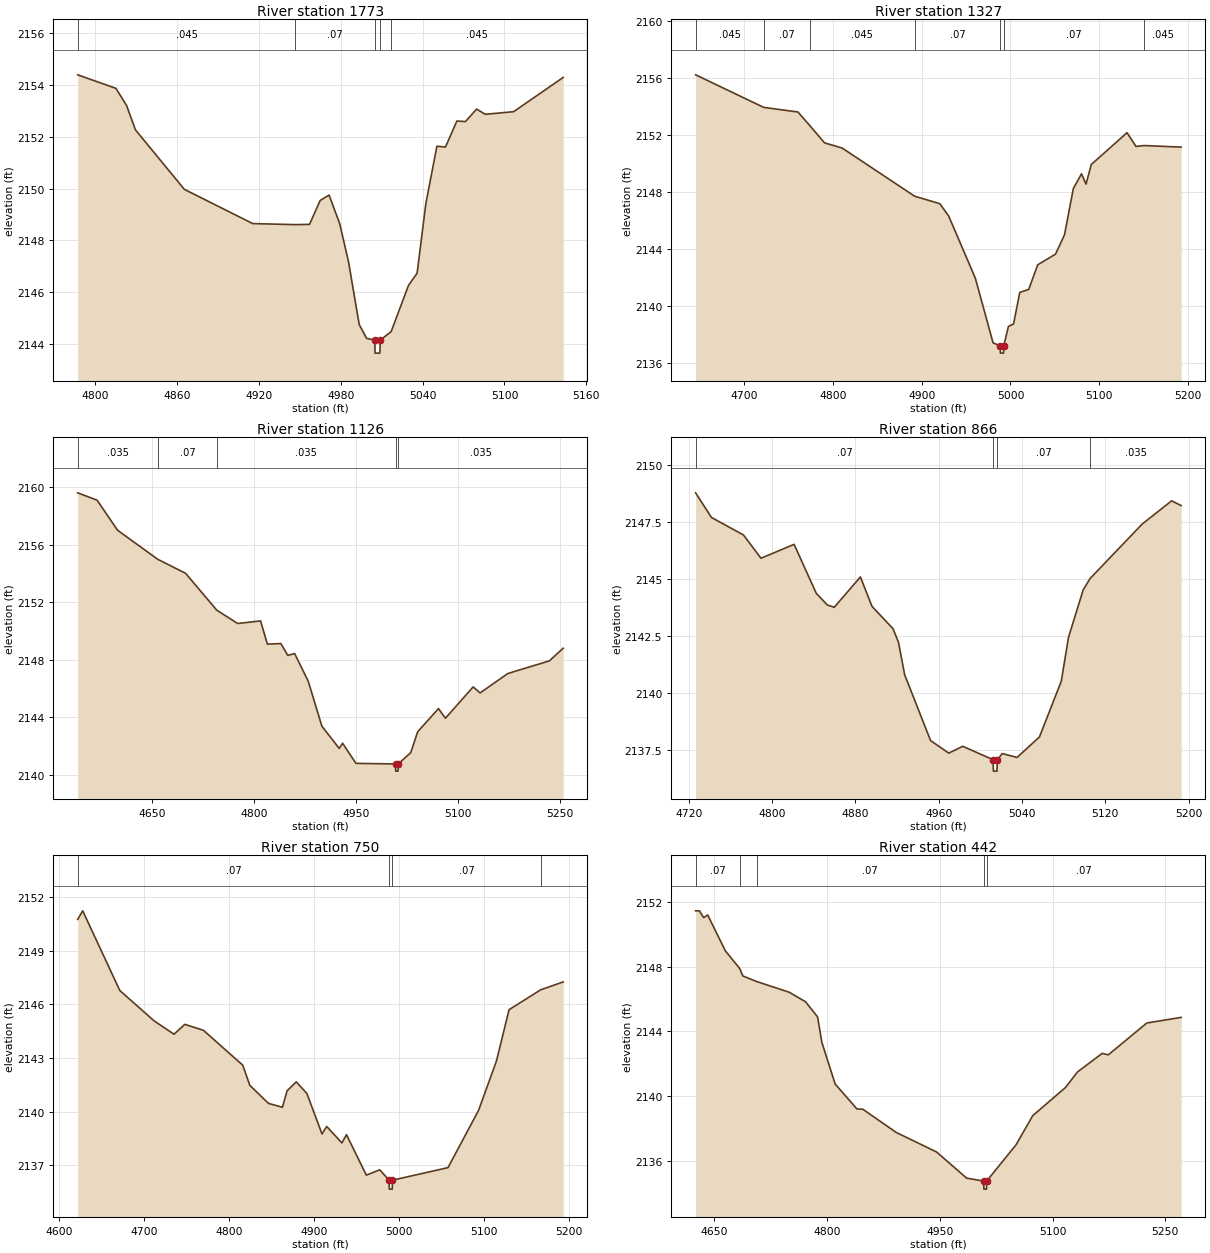
Type RM Length L Ch R = 1,1773,446,446,446
BEGIN DESCRIPTION:
Salt Branch Trib2 2.0
END DESCRIPTION:
XS GIS Cut Line= 3
      1381105.03      6836487.98      1381268.19      6836351.68
      1381354.98      6836238.03
#Sta/Elev= 30
  4787.4 2154.38  4815.4 2153.86  4823.2 2153.20  4829.7 2152.26  4865.5 2149.97
  4915.6 2148.65  4946.9 2148.61  4957.2 2148.62  4965.0 2149.54  4971.5 2149.75
  4979.3 2148.65  4985.8 2147.17  4993.6 2144.76  4999.0 2144.23  5005.0 2144.16
  5005.2 2143.66  5008.7 2143.66  5009.0 2144.16  5017.0 2144.49  5029.7 2146.27
  5036.0 2146.74  5042.4 2149.42  5050.5 2151.63  5056.8 2151.60  5065.1 2152.60
  5071.4 2152.58  5079.6 2153.06  5085.9 2152.86  5106.7 2152.96  5143.0 2154.28
#Mann=5,-1,0
  4787.4   0.045       0  4946.9    0.07       0  5005.0    0.07       0
  5009.0    0.07       0  5017.0   0.045       0
Bank Sta=5005,5009
Exp/Cntr=0.3,0.1

Type RM Length L Ch R = 1,1327,201,201,201
BEGIN DESCRIPTION:
Salt Branch Trib2 1.0
END DESCRIPTION:
XS GIS Cut Line= 3
      1381149.75      6836660.61      1381504.57      6836653.18
      1381695.57      6836629.95
#Sta/Elev= 30
  4645.1 2156.20  4721.9 2153.92  4760.4 2153.60  4773.9 2152.64  4790.4 2151.44
  4810.4 2151.07  4892.1 2147.70  4920.4 2147.18  4930.4 2146.31  4960.4 2141.97
  4980.4 2137.44  4988.4 2137.22  4988.7 2136.72  4992.2 2136.72  4992.4 2137.22
  4997.7 2138.59  5003.5 2138.76  5010.5 2140.97  5020.6 2141.18  5030.7 2142.90
  5050.8 2143.65  5060.9 2145.00  5070.9 2148.24  5080.1 2149.27  5085.2 2148.55
  5091.1 2149.92  5131.4 2152.15  5141.5 2151.19  5150.7 2151.25  5192.4 2151.14
#Mann=7,-1,0
  4645.1   0.045       0  4721.9    0.07       0  4773.9   0.045       0
  4892.1    0.07       0  4988.4    0.07       0  4992.4    0.07       0
  5150.7   0.045       0
Bank Sta=4988.4,4992.4
Exp/Cntr=0.3,0.1

Type RM Length L Ch R = 1,1126,260,260,260
BEGIN DESCRIPTION:
Salt Branch Trib2 2684
END DESCRIPTION:
XS GIS Cut Line= 3
      1381096.56      6836807.03      1381555.00      6836838.00
      1381804.97      6836887.99
#Sta/Elev= 30
  4540.4 2159.61  4568.9 2159.10  4599.0 2157.01  4658.4 2154.98  4699.2 2154.01
  4745.0 2151.45  4775.8 2150.52  4809.5 2150.70  4819.5 2149.09  4839.5 2149.12
  4849.5 2148.30  4859.6 2148.43  4879.6 2146.51  4899.7 2143.38  4925.2 2141.83
  4930.2 2142.19  4949.8 2140.79  5008.1 2140.75  5008.3 2140.25  5011.8 2140.25
  5012.1 2140.75  5030.5 2141.54  5040.7 2142.99  5071.3 2144.60  5081.5 2143.93
  5122.3 2146.11  5132.5 2145.69  5173.3 2147.04  5234.4 2147.92  5254.8 2148.80
#Mann=5,-1,0
  4540.4   0.035       0  4658.4    0.07       0  4745.0   0.035       0
  5008.1   0.035       0  5012.1   0.035       0
Bank Sta=5008.1,5012.1
Exp/Cntr=0.3,0.1

Type RM Length L Ch R = 1,866,116,116,116
BEGIN DESCRIPTION:
Salt Branch Trib2 4149
END DESCRIPTION:
XS GIS Cut Line= 3
      1381445.84      6837128.14      1381703.52      6837036.47
      1381844.21      6836904.50
#Sta/Elev= 30
  4726.5 2148.78  4741.7 2147.70  4772.5 2146.93  4789.3 2145.91  4821.1 2146.52
  4842.4 2144.37  4853.0 2143.86  4859.7 2143.76  4884.8 2145.09  4895.9 2143.80
  4916.1 2142.82  4921.4 2142.22  4927.3 2140.80  4952.2 2137.91  4969.7 2137.36
  4983.1 2137.66  5012.3 2137.07  5012.5 2136.57  5016.0 2136.57  5016.3 2137.07
  5021.1 2137.34  5035.3 2137.17  5056.8 2138.07  5077.8 2140.52  5084.7 2142.44
  5098.8 2144.52  5105.4 2145.02  5155.5 2147.41  5183.8 2148.43  5192.9 2148.22
#Mann=4,-1,0
  4726.5    0.07       0  5012.3    0.07       0  5016.3    0.07       0
  5105.4   0.035       0
Bank Sta=5012.3,5016.3
Exp/Cntr=0.3,0.1

Type RM Length L Ch R = 1,750,308,308,308
BEGIN DESCRIPTION:
Salt Branch Trib2 4148
END DESCRIPTION:
XS GIS Cut Line= 3
      1381439.59      6837270.24      1381785.40      6837117.84
      1381893.63      6836957.31
#Sta/Elev= 30
  4622.1 2150.74  4628.0 2151.22  4671.7 2146.77  4712.2 2145.07  4735.5 2144.33
  4748.2 2144.88  4770.1 2144.55  4816.4 2142.60  4824.7 2141.48  4846.6 2140.47
  4863.1 2140.25  4868.6 2141.17  4879.4 2141.67  4891.9 2141.02  4909.7 2138.76
  4915.2 2139.18  4933.1 2138.26  4938.5 2138.72  4961.9 2136.46  4977.7 2136.76
  4988.6 2136.18  4988.9 2135.68  4992.4 2135.68  4992.6 2136.18  5058.0 2136.88
  5094.0 2140.08  5115.0 2142.83  5129.9 2145.70  5167.1 2146.81  5193.6 2147.25
#Mann=4,-1,0
  4622.1    0.07       0  4988.6    0.07       0  4992.6    0.07       0
  5167.1   0.035       0
Bank Sta=4988.6,4992.6
Exp/Cntr=0.3,0.1

Type RM Length L Ch R = 1,442,104,104,104
BEGIN DESCRIPTION:
Salt Branch Trib2 4147
END DESCRIPTION:
XS GIS Cut Line= 3
      1381520.93      6837547.58      1381864.84      6837398.08
      1381923.28      6837133.36
#Sta/Elev= 30
  4625.0 2151.47  4630.0 2151.47  4635.7 2151.05  4641.1 2151.21  4664.6 2148.99
  4683.6 2147.90  4688.0 2147.43  4706.3 2147.09  4749.4 2146.43  4771.2 2145.84
  4787.3 2144.90  4793.0 2143.32  4810.7 2140.74  4839.6 2139.20  4847.5 2139.18
  4892.0 2137.74  4945.7 2136.53  4985.7 2134.91  5008.3 2134.73  5008.6 2134.23
  5012.1 2134.23  5012.3 2134.73  5051.3 2136.97  5073.6 2138.78  5117.3 2140.53
  5133.2 2141.49  5166.1 2142.64  5174.2 2142.55  5225.4 2144.52  5271.1 2144.87
#Mann=5,-1,0
  4625.0    0.07       0  4683.6   0.035       0  4706.3    0.07       0
  5008.3    0.07       0  5012.3    0.07       0
Bank Sta=5008.3,5012.3
Exp/Cntr=0.3,0.1

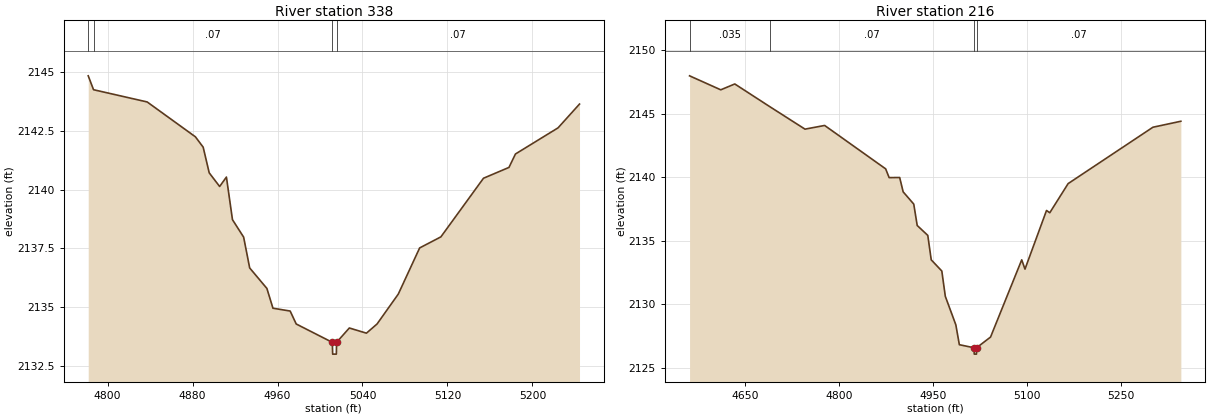
Type RM Length L Ch R = 1,338,122,122,122
BEGIN DESCRIPTION:
 Salt Branch Trib2 4179
END DESCRIPTION:
XS GIS Cut Line= 3
      1381746.12      6837575.04      1381938.23      6837471.57
      1381954.49      6837227.81
#Sta/Elev= 30
  4781.8 2144.83  4786.8 2144.24  4837.3 2143.72  4882.7 2142.24  4890.0 2141.80
  4895.7 2140.71  4905.5 2140.13  4911.9 2140.53  4917.6 2138.72  4928.1 2137.98
  4933.8 2136.67  4950.0 2135.80  4955.7 2134.96  4971.9 2134.84  4977.6 2134.29
  5011.6 2133.51  5011.9 2133.01  5015.4 2133.01  5015.6 2133.51  5027.6 2134.12
  5043.7 2133.90  5053.7 2134.29  5073.7 2135.56  5093.8 2137.52  5113.8 2137.99
  5153.9 2140.48  5177.9 2140.94  5184.0 2141.51  5224.1 2142.62  5244.3 2143.63
#Mann=4,-1,0
  4781.8   0.035       0  4786.8    0.07       0  5011.6    0.07       0
  5015.6    0.07       0
Bank Sta=5011.6,5015.6
Exp/Cntr=0.3,0.1

Type RM Length L Ch R = 1,216,0,0,0
BEGIN DESCRIPTION:
Salt Branch Trib2 4091
END DESCRIPTION:
XS GIS Cut Line= 3
      1381661.79      6837683.36      1382055.00      6837488.15
      1381963.62      6837154.96
#Sta/Elev= 30
  4561.0 2147.97  4610.8 2146.87  4633.2 2147.33  4688.7 2145.56  4745.3 2143.78
  4776.7 2144.07  4874.1 2140.66  4879.7 2139.97  4896.5 2139.98  4902.1 2138.85
  4919.0 2137.89  4924.5 2136.21  4941.4 2135.43  4946.9 2133.51  4963.8 2132.63
  4969.4 2130.64  4986.2 2128.40  4991.8 2126.84  5015.3 2126.60  5015.6 2126.10
  5019.1 2126.10  5019.3 2126.60  5041.6 2127.44  5091.4 2133.51  5096.6 2132.78
  5131.0 2137.39  5136.2 2137.21  5165.5 2139.50  5300.9 2143.93  5345.5 2144.40
#Mann=4,-1,0
  4561.0   0.035       0  4688.7    0.07       0  5015.3    0.07       0
  5019.3    0.07       0
Bank Sta=5015.3,5019.3
Exp/Cntr=0.3,0.1

Chan Stop Cuts=-1