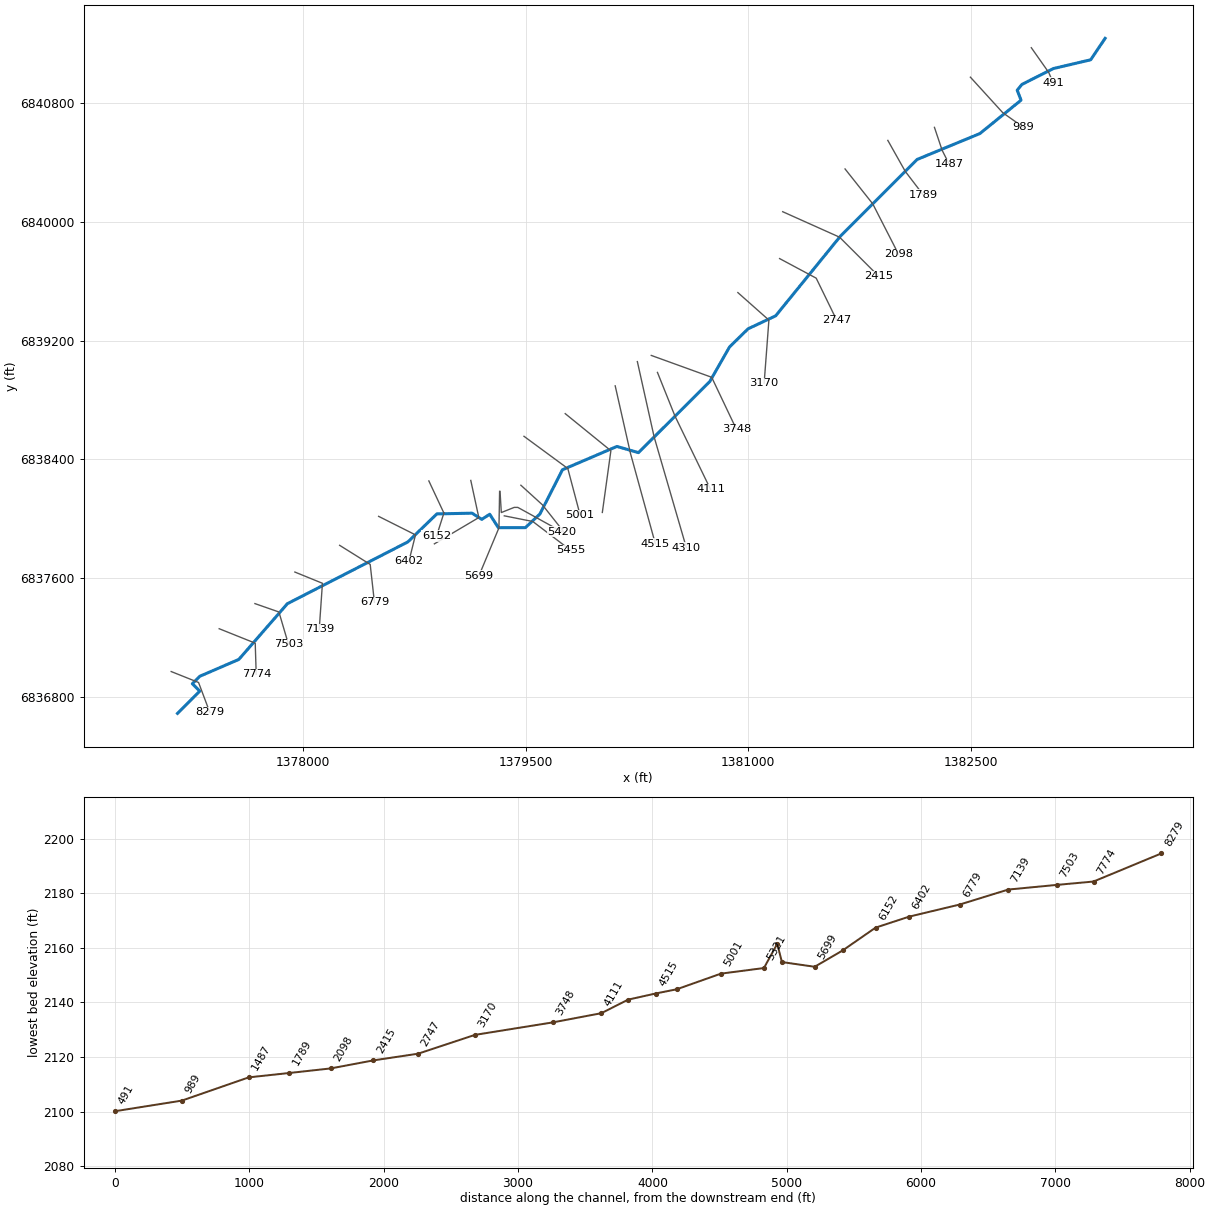
--- Salt Branch Trib3.prj (project) ---

Proj Title=Salt Branch Trib3 Base Level Engineering
Current Plan=p01
Default Exp/Contr=0.3,0.1
English Units
Geom File=g01
Flow File=f01
Plan File=p01
Y Axis Title=Elevation
X Axis Title(PF)=Main Channel Distance
X Axis Title(XS)=Station
BEGIN DESCRIPTION:
Salt Branch Trib3
END DESCRIPTION:
DSS Export Rating Curves= 0
DSS Export Rating Curve Sorted= 0
DSS Export Volume Flow Curves= 0
DXF OffsetX= 0
DXF OffsetY= 0
DXF ScaleX= 1
DXF ScaleY= 10

--- Salt Branch Trib3.p01 (plan) ---

Plan Title=Multiple Run
Short Identifier=Multiple
Geom File=g01
Flow File=f01
Subcritical Flow
K Sum by GR= 0
Std Step Tol= 0.01
Critical Tol= 0.01
Num of Std Step Trials= 20
Max Error Tol= 0.3
Flow Tol Ratio= 0.001
Split Flow NTrial= 30
Split Flow Tol= 0.02
Split Flow Ratio= 0.02
Log Output Level= 0
Friction Slope Method= 1
Unsteady Friction Slope Method= 2
Unsteady Bridges Friction Slope Method= 1
Parabolic Critical Depth
Global Vel Dist=  1 , 1 , 1
Global Log Level= 0
CheckData=True
Encroach Param= -1, 0, 0, 0
BEGIN DESCRIPTION:
Multiple Run
END DESCRIPTION:

--- Salt Branch Trib3.f01 (steady flow) ---

Flow Title=Multiple
Number of Profiles=7
Profile Names=10-year,25-year,50-year,1pct_min,100-year,1pct_plu,500-year
River Rch & RM= Salt Branch Trib,Reach-1,8279
     198     278     344     212     424     845     651
River Rch & RM= Salt Branch Trib,Reach-1,4310
     275     392     491     306     611    1219     958
Boundary for River Rch & Prof#=Salt Branch Trib,Reach-1,1
Up Type=0
Dn Type=3
Dn Slope=0.005
Boundary for River Rch & Prof#=Salt Branch Trib,Reach-1,2
Up Type=0
Dn Type=3
Dn Slope=0.005
Boundary for River Rch & Prof#=Salt Branch Trib,Reach-1,3
Up Type=0
Dn Type=3
Dn Slope=0.005
Boundary for River Rch & Prof#=Salt Branch Trib,Reach-1,4
Up Type=0
Dn Type=3
Dn Slope=0.005
Boundary for River Rch & Prof#=Salt Branch Trib,Reach-1,5
Up Type=0
Dn Type=3
Dn Slope=0.005
Boundary for River Rch & Prof#=Salt Branch Trib,Reach-1,6
Up Type=0
Dn Type=3
Dn Slope=0.005
Boundary for River Rch & Prof#=Salt Branch Trib,Reach-1,7
Up Type=0
Dn Type=3
Dn Slope=0.005

--- Salt Branch Trib3.g01 (geometry) ---

Geom Title=Existing Conditions
Program Version=4.10

River Reach=Salt Branch Trib,Reach-1
Reach XY= 30
        1377155.        6836688.        1377305.        6836838.
        1377255.        6836888.        1377305.        6836938.
      1377568.22      6837051.62      1377895.32      6837427.24
       1378707.3      6837843.83      1378902.55      6838032.54
      1379139.84      6838037.35      1379205.11      6837995.81
      1379258.57      6838030.07      1379316.83      6837939.66
      1379499.16      6837940.05      1379596.87      6838031.93
      1379748.66      6838329.98      1380115.69      6838487.23
      1380261.06      6838445.48      1380741.37      6838924.79
      1380874.79      6839158.09      1380998.94      6839279.86
      1381185.16      6839367.61      1381621.65      6839904.67
      1382138.25      6840421.54      1382561.06      6840596.14
      1382838.62       6840821.3      1382812.46      6840888.24
      1382844.51      6840927.48       1383056.5      6841034.38
      1383307.68      6841093.41        1383405.        6841238.

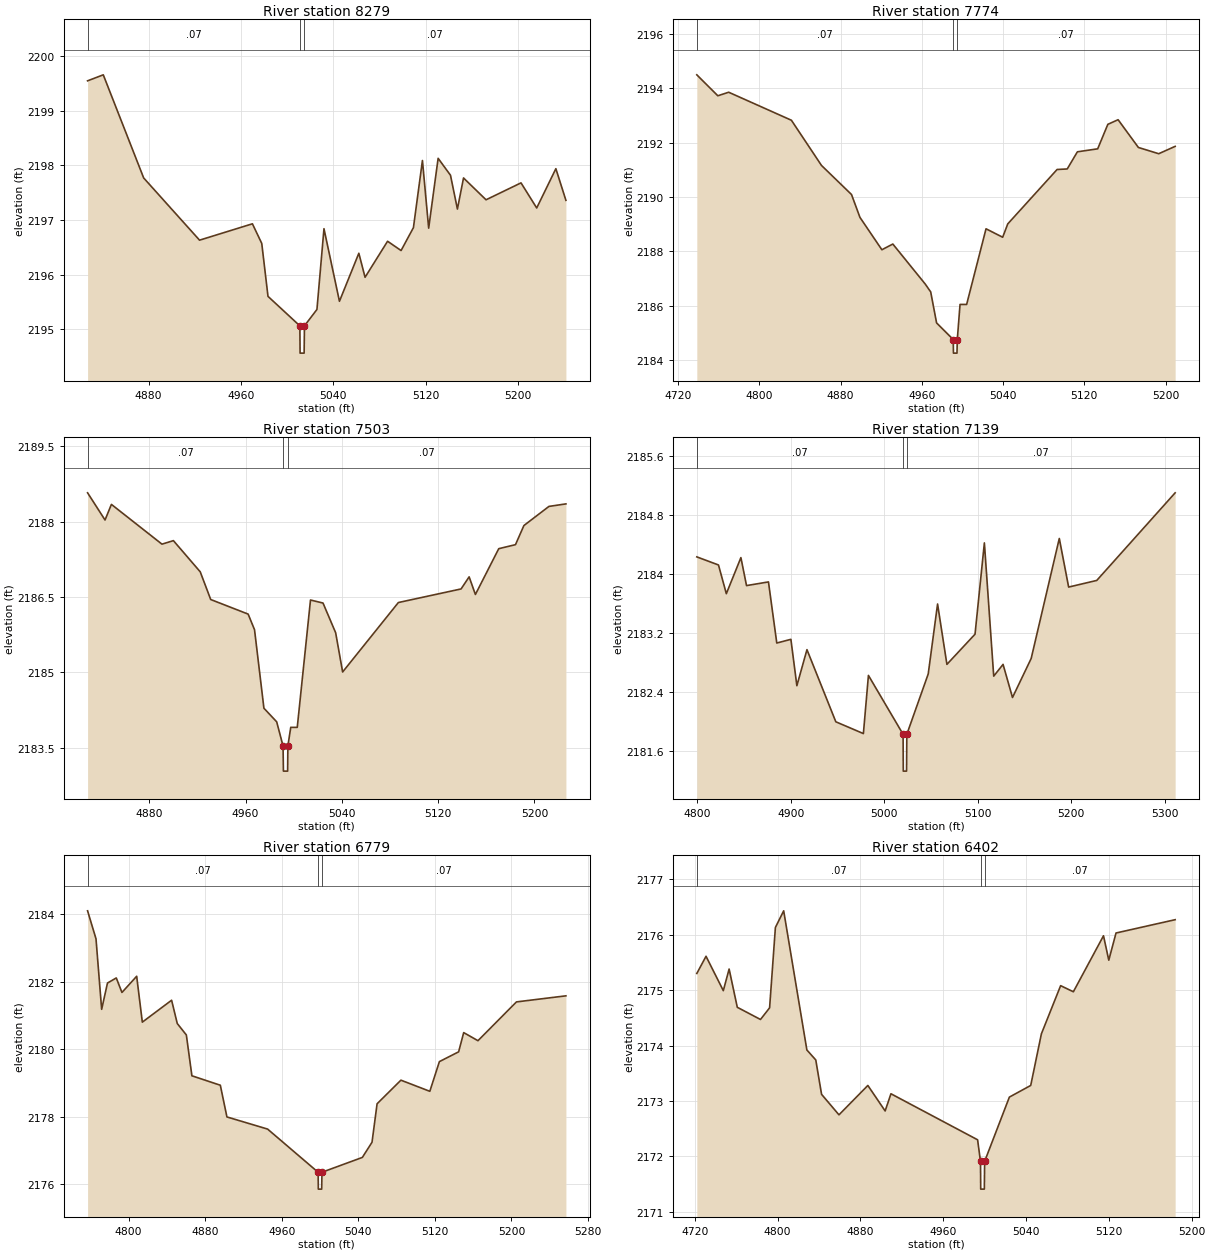
Type RM Length L Ch R = 1 ,8279    ,505,505,505
BEGIN DESCRIPTION:
Salt Branch Trib3 4241
END DESCRIPTION:
XS GIS Cut Line= 3
      1377112.41      6836970.03      1377296.92      6836896.23
      1377372.89      6836694.37
#Sta/Elev= 30
  4827.2 2199.55  4840.8 2199.66  4875.8 2197.77  4924.2 2196.63    4970 2196.93
  4978.1 2196.57  4983.5  2195.6  5011.1 2195.06  5011.3 2194.56  5014.8 2194.56
  5015.1 2195.06  5025.9 2195.36    5032 2196.84  5045.4 2195.51  5062.2 2196.39
  5067.6 2195.95  5087.1 2196.61  5098.8 2196.44  5109.5 2196.86  5117.3 2198.09
  5122.7 2196.85  5130.9 2198.13  5141.6 2197.82  5147.6  2197.2  5152.9 2197.77
  5172.4 2197.37  5202.7 2197.68  5216.3 2197.22  5232.9 2197.94  5241.6 2197.36
#Mann= 3 ,-1 , 0
  4827.2     .07       0  5011.1     .07       0  5015.1     .07       0
Bank Sta=5011.1,5015.1
XS Rating Curve= 0 ,0
Exp/Cntr=0.3,0.1

Type RM Length L Ch R = 1 ,7774    ,271,271,271
BEGIN DESCRIPTION:
Salt Branch Trib3 4240
END DESCRIPTION:
XS GIS Cut Line= 3
      1377435.83      6837258.63       1377678.7      6837161.18
      1377685.33      6836951.78
#Sta/Elev= 30
  4738.3 2194.49    4759 2193.72  4769.7 2193.85  4831.5 2192.82  4861.1 2191.16
  4890.7 2190.09    4899 2189.25  4920.6 2188.06  4931.4 2188.27  4963.3  2186.8
  4968.7 2186.51  4974.5 2185.37  4990.9 2184.76  4991.1 2184.26  4994.6 2184.26
  4994.9 2184.76  4997.6 2186.05  5004.1 2186.05  5023.2 2188.83  5039.6 2188.52
  5044.6 2189.01  5093.2 2191.01  5103.2 2191.03  5113.2 2191.66  5133.2 2191.77
  5143.2 2192.67  5153.3 2192.84  5173.3 2191.82  5193.3 2191.59  5209.5 2191.86
#Mann= 3 ,-1 , 0
  4738.3     .07       0  4990.9     .07       0  4994.9     .07       0
Bank Sta=4990.9,4994.9
XS Rating Curve= 0 ,0
Exp/Cntr=0.3,0.1

Type RM Length L Ch R = 1 ,7503    ,364,364,364
BEGIN DESCRIPTION:
Salt Branch Trib3 4239
END DESCRIPTION:
XS GIS Cut Line= 3
      1377676.68      6837427.92       1377838.3      6837371.42
      1377902.38      6837154.49
#Sta/Elev= 30
  4828.8 2188.57  4843.3 2188.03  4848.6 2188.34  4890.6 2187.55  4900.1 2187.62
  4922.4    2187  4931.1 2186.45  4962.2 2186.16  4967.5 2185.85  4975.3 2184.29
  4985.9 2184.02  4991.2 2183.54  4991.5 2183.04    4995 2183.04  4995.2 2183.54
  4997.6 2183.91    5003 2183.91    5014 2186.44  5024.4 2186.38  5034.9 2185.79
  5040.7 2185.01    5087 2186.39  5139.1 2186.66  5145.8  2186.9    5151 2186.55
  5170.4 2187.46  5184.3 2187.54  5191.3 2187.92  5212.1  2188.3  5226.2 2188.35
#Mann= 3 ,-1 , 0
  4828.8     .07       0  4991.2     .07       0  4995.2     .07       0
Bank Sta=4991.2,4995.2
XS Rating Curve= 0 ,0
Exp/Cntr=0.3,0.1

Type RM Length L Ch R = 1 ,7139    ,360,360,360
BEGIN DESCRIPTION:
Salt Branch Trib3 4238
END DESCRIPTION:
XS GIS Cut Line= 3
      1377945.77       6837640.6      1378131.55      6837564.94
       1378109.9       6837254.3
#Sta/Elev= 30
  4799.4 2184.23  4822.6 2184.12    4831 2183.73  4846.6 2184.22  4852.6 2183.84
  4876.1 2183.89    4885 2183.06  4900.1 2183.11  4906.5 2182.48  4917.3 2182.97
  4948.2 2181.99  4977.7 2181.83  4983.1 2182.62  5020.2 2181.82  5020.4 2181.32
  5023.9 2181.32  5024.2 2181.82  5047.1 2182.64  5057.1 2183.59  5067.1 2182.77
  5097.2 2183.18  5107.2 2184.42  5117.2 2182.61  5127.2 2182.77  5137.3 2182.32
  5157.3 2182.85  5187.4 2184.48  5197.4 2183.82  5227.5 2183.91  5311.4  2185.1
#Mann= 3 ,-1 , 0
  4799.4     .07       0  5020.2     .07       0  5024.2     .07       0
Bank Sta=5020.2,5024.2
XS Rating Curve= 0 ,0
Exp/Cntr=0.3,0.1

Type RM Length L Ch R = 1 ,6779    ,377,377,377
BEGIN DESCRIPTION:
Salt Branch Trib3 4237
END DESCRIPTION:
XS GIS Cut Line= 3
      1378247.41      6837820.73      1378453.36      6837691.96
      1378481.81      6837436.64
#Sta/Elev= 30
  4757.1  2184.1  4765.9 2183.27  4771.8 2181.18  4777.9 2181.96  4787.1 2182.11
    4793 2181.68  4808.4 2182.16  4814.3  2180.8  4844.9 2181.45  4850.8 2180.76
  4860.3 2180.42  4866.1 2179.21  4895.8 2178.93  4902.7 2177.99  4945.2 2177.63
    4998 2176.35  4998.2 2175.85  5001.7 2175.85    5002 2176.35  5044.2 2176.79
  5054.3 2177.24  5059.6 2178.38  5084.5 2179.08  5114.7 2178.75  5124.7 2179.63
  5144.8 2179.92  5150.1 2180.49    5165 2180.25  5205.2  2181.4  5256.9 2181.58
#Mann= 3 ,-1 , 0
  4757.1     .07       0    4998     .07       0    5002     .07       0
Bank Sta=4998,5002
XS Rating Curve= 0 ,0
Exp/Cntr=0.3,0.1

Type RM Length L Ch R = 1 ,6402    ,250,250,250
BEGIN DESCRIPTION:
Salt Branch Trib3 4236
END DESCRIPTION:
XS GIS Cut Line= 3
      1378510.06        6838016.      1378758.46      6837891.17
      1378714.12       6837712.6
#Sta/Elev= 30
    4722  2175.3  4730.9 2175.61  4747.6 2174.99  4753.2 2175.38  4761.1 2174.69
  4783.5 2174.47  4792.3 2174.68  4797.9 2176.13  4805.9 2176.43  4828.3 2173.92
  4836.9 2173.74  4842.5 2173.12  4859.3 2172.75  4887.2 2173.28  4903.9 2172.82
  4909.5 2173.13  4993.2  2172.3    4996 2171.91  4996.2 2171.41  4999.7 2171.41
    5000 2171.91  5023.9 2173.07  5044.5 2173.28  5054.8 2174.21  5073.4 2175.08
  5085.7 2174.97  5114.8 2175.98  5119.9 2175.54  5126.9 2176.03    5184 2176.27
#Mann= 3 ,-1 , 0
    4722     .07       0    4996     .07       0    5000     .07       0
Bank Sta=4996,5000
XS Rating Curve= 0 ,0
Exp/Cntr=0.3,0.1

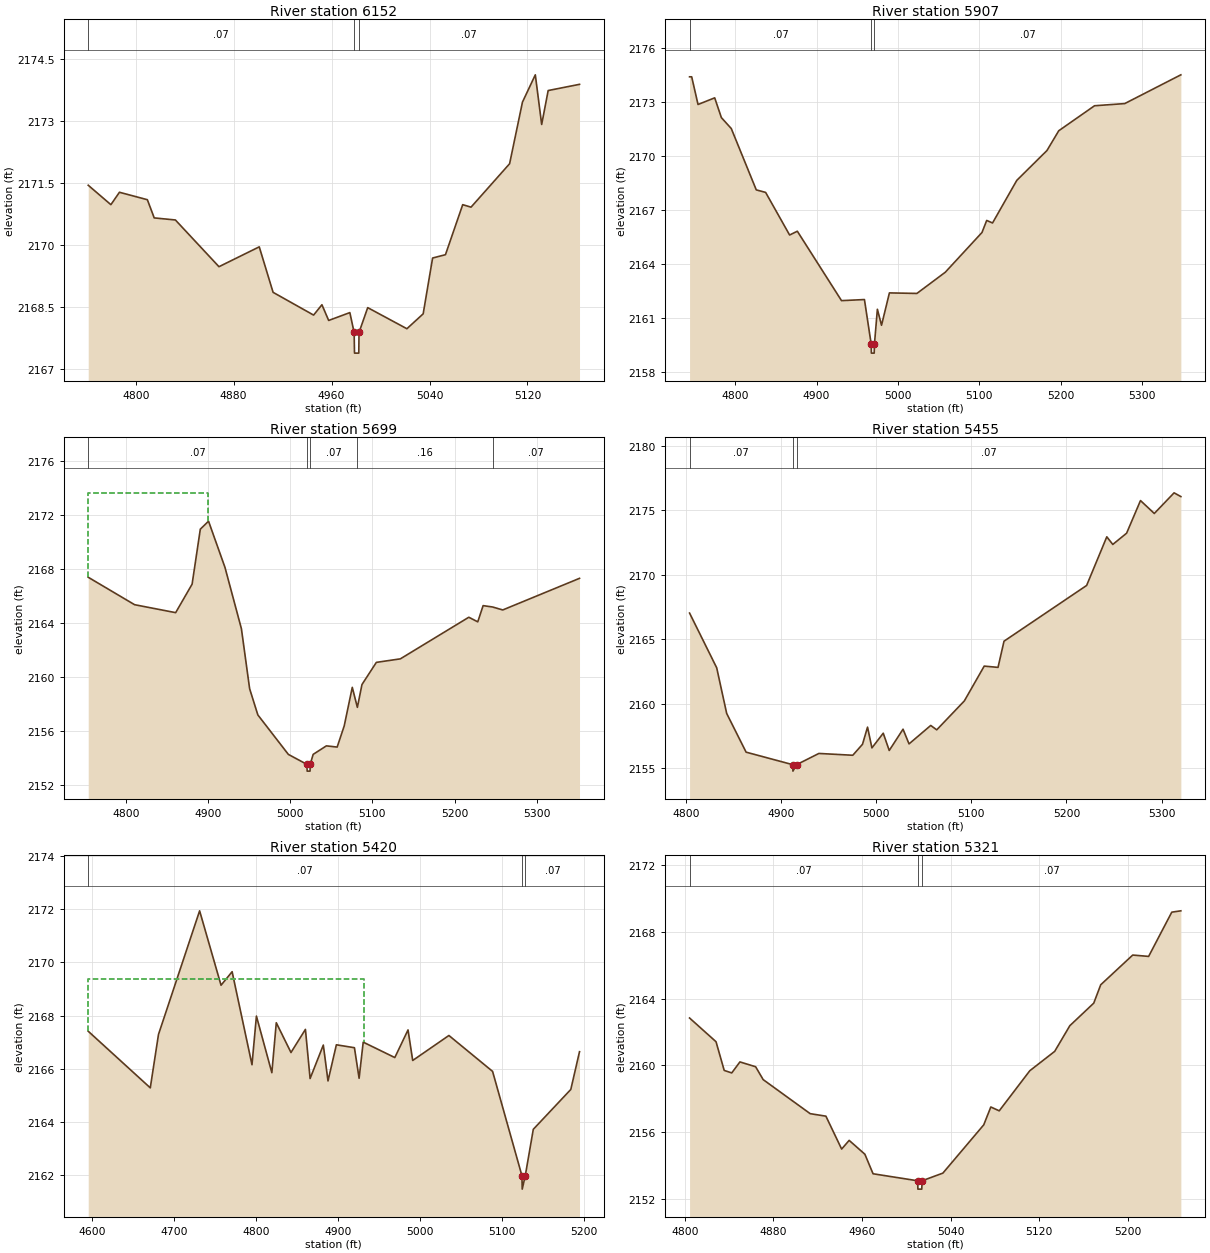
Type RM Length L Ch R = 1 ,6152    ,245,245,245
BEGIN DESCRIPTION:
Salt Branch Trib3 4235
END DESCRIPTION:
XS GIS Cut Line= 3
      1378848.56      6838254.75       1378949.8      6838038.48
      1378900.64       6837883.6
#Sta/Elev= 30
  4761.2 2171.44  4779.7 2170.97  4786.7 2171.27  4809.5 2171.09  4815.1 2170.65
  4832.4  2170.6    4868 2169.47  4900.9 2169.95  4912.2 2168.85  4945.3  2168.3
  4952.1 2168.55  4957.6 2168.17  4974.9 2168.36  4978.4 2167.88  4978.7 2167.38
  4982.2 2167.38  4982.4 2167.88  4989.5 2168.48  5021.5 2167.97  5034.8 2168.33
  5042.5 2169.68    5053 2169.76  5067.1 2170.97  5073.9 2170.91  5105.4 2171.96
  5115.9 2173.45  5126.4 2174.11  5131.6 2172.91  5136.9 2173.73  5162.5 2173.88
#Mann= 3 ,-1 , 0
  4761.2     .07       0  4978.4     .07       0  4982.4     .07       0
Bank Sta=4978.4,4982.4
XS Rating Curve= 0 ,0
Exp/Cntr=0.3,0.1

Type RM Length L Ch R = 1 ,5907    ,208,208,208
BEGIN DESCRIPTION:
Salt Branch Trib3 4234
END DESCRIPTION:
XS GIS Cut Line= 3
      1379131.05      6838258.18      1379185.21      6838007.87
      1378885.81      6837830.68
#Sta/Elev= 30
  4743.9  2174.4  4746.5  2174.4  4754.3 2172.86  4774.8 2173.23    4783 2172.13
  4795.2 2171.52  4825.9 2168.11  4837.4 2167.97  4866.9  2165.6  4876.4 2165.81
  4930.7 2161.95  4958.9 2162.01  4967.2 2159.53  4967.4 2159.03  4970.9 2159.03
  4971.2 2159.53  4974.8 2161.47  4979.9 2160.58  4989.6 2162.38  5023.4 2162.35
  5058.3 2163.53  5103.4 2165.74  5109.2 2166.41  5116.4 2166.27  5146.2 2168.64
  5183.3  2170.3  5197.8  2171.4  5241.8 2172.79  5278.9 2172.91  5347.9 2174.51
#Mann= 3 ,-1 , 0
  4743.9     .07       0  4967.2     .07       0  4971.2     .07       0
Bank Sta=4967.2,4971.2
XS Rating Curve= 0 ,0
Exp/Cntr=0.3,0.1

Type RM Length L Ch R = 1 ,5699    ,244,244,244
BEGIN DESCRIPTION:
Salt Branch Trib3 4233
END DESCRIPTION:
XS GIS Cut Line= 3
      1379325.23      6838184.35      1379320.84      6837938.69
      1379185.32      6837613.72
#Sta/Elev= 30
  4754.3 2167.41  4810.7 2165.38  4860.7 2164.79  4880.7  2166.9  4890.7 2170.97
  4900.7 2171.56  4920.7 2168.14  4940.7  2163.6  4950.7 2159.16  4960.7 2157.22
  4997.8  2154.3  5020.4 2153.56  5020.7 2153.06  5024.2 2153.06  5024.4 2153.56
    5028  2154.3  5044.1 2154.93  5057.2 2154.84  5065.8 2156.41  5075.6 2159.26
  5081.8 2157.78  5087.4 2159.47  5104.9 2161.11  5134.1 2161.37  5217.4 2164.45
  5228.3 2164.11  5234.8 2165.31  5246.3 2165.21  5258.7 2164.99  5352.1 2167.33
#Mann= 5 ,-1 , 0
  4754.3     .07       0  5020.4     .07       0  5024.4     .07       0
  5081.8     .16       0  5246.3     .07       0
#XS Ineff= 2 , 0
         4900.41 2173.66
Permanent Ineff=
       F       F
Bank Sta=5020.4,5024.4
XS Rating Curve= 0 ,0
Exp/Cntr=0.3,0.1

Type RM Length L Ch R = 1 ,5455    ,35,35,35
BEGIN DESCRIPTION:
Salt Branch Trib3 4232
END DESCRIPTION:
XS GIS Cut Line= 3
      1379356.76      6838019.49      1379549.01       6837981.3
      1379803.76      6837787.31
#Sta/Elev= 30
    4804 2167.03  4832.5 2162.79    4843 2159.25  4863.4 2156.25  4912.4 2155.28
  4912.6 2154.78  4916.4 2155.28  4939.9 2156.15  4975.5 2156.01  4985.7 2156.86
    4991 2158.19  4995.6 2156.58  5007.5 2157.72  5013.8 2156.38  5028.3 2158.03
  5034.6 2156.89  5057.4 2158.32  5063.7 2157.98  5092.7 2160.22  5113.6 2162.92
  5128.1 2162.82  5134.4 2164.85  5221.2 2169.17  5242.4 2172.94  5248.7 2172.35
  5263.2 2173.22  5277.8 2175.75  5292.3 2174.75  5313.1 2176.35  5320.2 2176.06
#Mann= 3 ,-1 , 0
    4804     .07       0  4912.4     .07       0  4916.4     .07       0
Bank Sta=4912.4,4916.4
XS Rating Curve= 0 ,0
Exp/Cntr=0.3,0.1

Type RM Length L Ch R = 1 ,5420    ,99,99,99
BEGIN DESCRIPTION:
Salt Branch Trib3 4231
END DESCRIPTION:
XS GIS Cut Line= 6
      1379328.26      6838183.48      1379336.72      6838041.66
      1379423.53      6838076.39      1379447.83      6838076.39
      1379517.28      6838038.19      1379744.24      6837912.63
#Sta/Elev= 30
  4595.7 2167.41  4671.3 2165.28  4681.3 2167.29  4731.4 2171.94  4757.5 2169.14
    4771 2169.65  4795.2 2166.15  4800.6 2167.98  4819.4 2165.85  4824.8 2167.73
  4842.7 2166.61  4860.3 2167.48    4866 2165.63  4882.1 2166.89  4887.8 2165.54
    4898  2166.9    4920 2166.79  4925.7 2165.64  4930.7    2167  4969.2 2166.42
  4985.3 2167.46    4991 2166.31  5035.1 2167.25  5088.3  2165.9  5124.1 2161.97
  5124.4 2161.47  5128.1 2161.97  5137.9 2163.72  5183.6 2165.22  5194.2 2166.64
#Mann= 3 ,-1 , 0
  4595.7     .07       0  5124.1     .07       0  5128.1     .07       0
#XS Ineff= 2 , 0
         4931.37 2169.36
Permanent Ineff=
       F       F
Bank Sta=5124.1,5128.1
XS Rating Curve= 0 ,0
Exp/Cntr=0.3,0.1

Type RM Length L Ch R = 1 ,5321    ,320,320,320
BEGIN DESCRIPTION:
Salt Branch Trib3 4230
END DESCRIPTION:
XS GIS Cut Line= 3
      1379468.64      6838225.72      1379613.44      6838093.93
      1379767.29      6837899.29
#Sta/Elev= 30
  4804.2 2162.84  4828.1 2161.42  4835.5  2159.7  4842.3 2159.55  4849.7 2160.21
  4863.9 2159.92  4870.7 2159.15  4913.2 2157.11  4927.4 2156.96  4941.6 2154.99
  4948.4 2155.51  4962.6 2154.68    4970 2153.51  5010.3 2153.09  5010.5 2152.59
    5014 2152.59  5014.3 2153.09  5033.1 2153.55    5070 2156.44  5076.4 2157.51
    5084 2157.28  5111.6 2159.68  5134.1 2160.84  5147.8 2162.38  5169.4 2163.73
  5175.7 2164.83  5204.6 2166.61    5219 2166.53  5239.9 2169.18  5248.1 2169.26
#Mann= 3 ,-1 , 0
  4804.2     .07       0  5010.3     .07       0  5014.3     .07       0
Bank Sta=5010.3,5014.3
XS Rating Curve= 0 ,0
Exp/Cntr=0.3,0.1

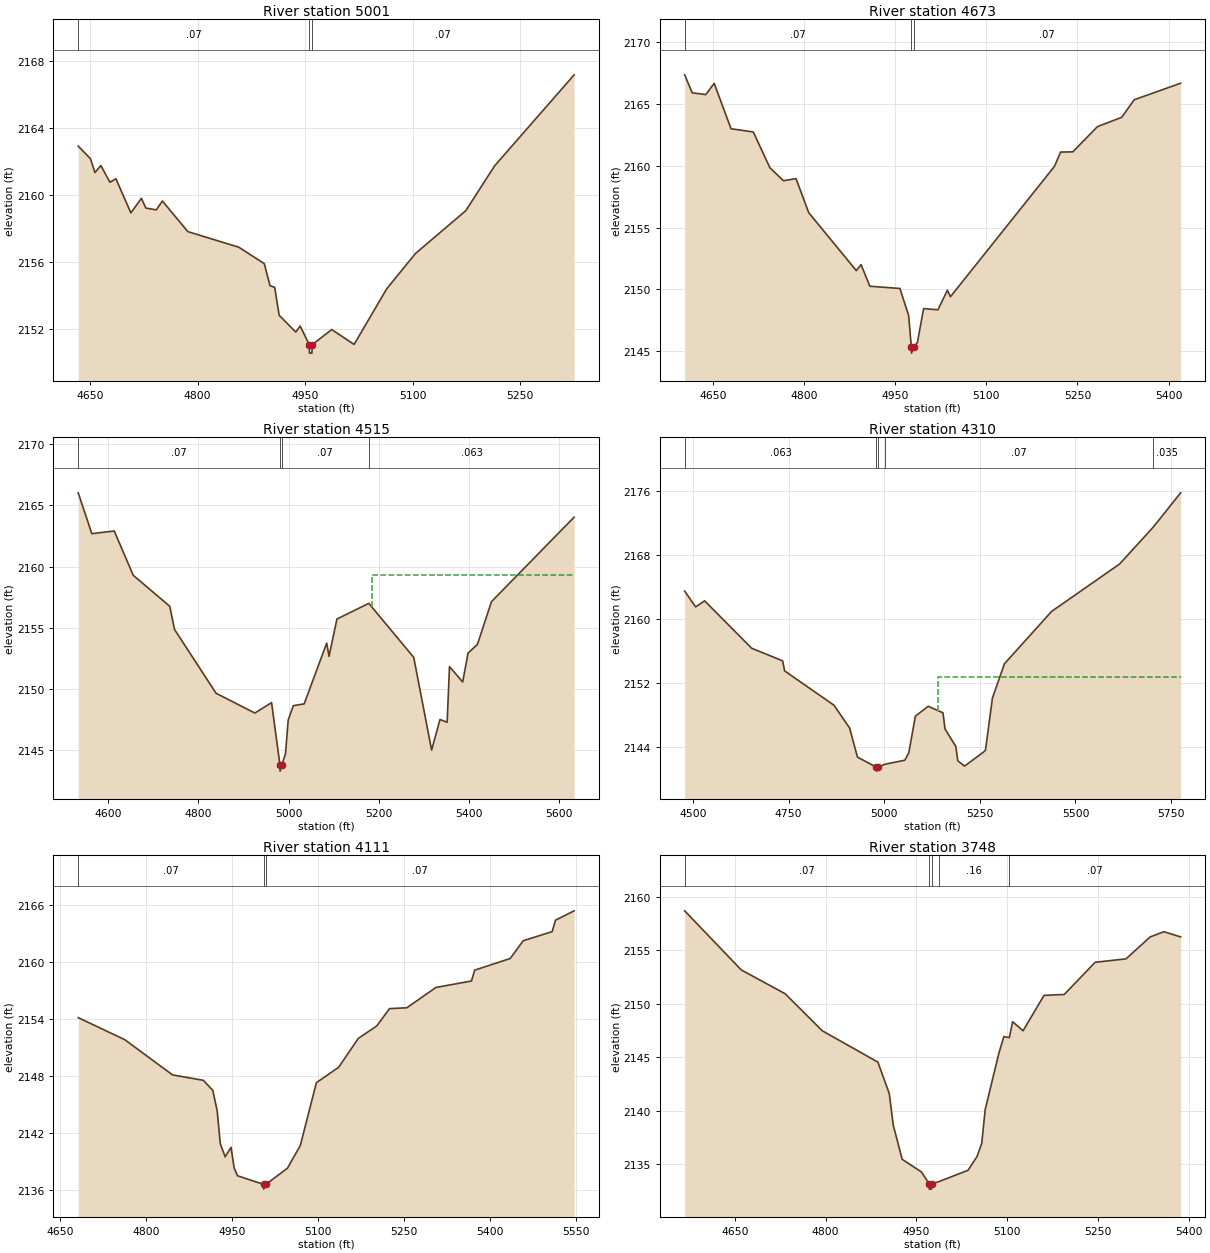
Type RM Length L Ch R = 1 ,5001    ,328,328,328
BEGIN DESCRIPTION:
Salt Branch Trib3 4229
END DESCRIPTION:
XS GIS Cut Line= 3
      1379489.51      6838555.54      1379784.73      6838338.52
      1379867.98      6838024.26
#Sta/Elev= 30
  4633.6 2162.91  4650.7 2162.16  4656.9 2161.33  4665.2 2161.75  4677.8 2160.75
  4686.2 2160.96    4707 2158.92  4721.7 2159.79  4727.9 2159.21  4742.5  2159.1
    4751 2159.63  4786.5  2157.8  4857.5 2156.87    4893 2155.89    4901 2154.57
  4907.6 2154.47  4913.8  2152.8  4936.9  2151.8  4943.1 2152.16  4955.8 2151.04
    4956 2150.54  4959.5 2150.54  4959.8 2151.04  4987.1 2151.95  5018.3 2151.06
  5063.7 2154.38    5104  2156.5    5174 2159.05  5214.2 2161.73  5325.1 2167.17
#Mann= 3 ,-1 , 0
  4633.6     .07       0  4955.8     .07       0  4959.8     .07       0
Bank Sta=4955.8,4959.8
XS Rating Curve= 0 ,0
Exp/Cntr=0.3,0.1

Type RM Length L Ch R = 1 ,4673    ,158,158,158
BEGIN DESCRIPTION:
Salt Branch Trib3 4228
END DESCRIPTION:
XS GIS Cut Line= 3
      1379767.31      6838708.31      1380074.99      6838458.22
      1380017.37       6838042.3
#Sta/Elev= 30
  4603.5 2167.38  4615.9 2165.92  4638.2 2165.78  4652.1 2166.69  4679.8 2163.01
  4716.5 2162.75  4743.7 2159.86    4766  2158.8  4786.8 2158.97  4807.7 2156.21
    4886 2151.52  4893.9    2152  4908.3 2150.25  4957.8 2150.07  4972.2 2147.88
  4976.6 2145.33  4976.9 2144.83  4980.6 2145.33  4986.6 2145.69  4996.8 2148.44
  5020.4 2148.34    5036 2149.93    5041  2149.4  5212.2 2159.96  5222.3 2161.12
  5242.5 2161.14  5282.9 2163.18    5323 2163.94  5343.5 2165.36  5419.9  2166.7
#Mann= 3 ,-1 , 0
  4603.5     .07       0  4976.6     .07       0  4980.6     .07       0
Bank Sta=4976.6,4980.6
XS Rating Curve= 0 ,0
Exp/Cntr=0.3,0.1

Type RM Length L Ch R = 1 ,4515    ,205,205,205
BEGIN DESCRIPTION:
Salt Branch Trib3 4227
END DESCRIPTION:
XS GIS Cut Line= 3
      1380104.08      6838895.82      1380206.74      6838441.37
      1380374.49      6837831.42
#Sta/Elev= 30
  4534.1 2166.03  4564.3 2162.69  4613.9 2162.91  4655.9 2159.29  4736.9 2156.75
  4747.4 2154.86  4839.4 2149.64  4925.3 2148.02  4962.4 2148.87    4981 2143.77
  4981.2 2143.27    4985 2143.77  4993.2 2144.68  4999.2 2147.44  5010.5 2148.62
  5034.6 2148.77  5084.5 2153.74  5089.7 2152.66  5107.2 2155.71  5177.8 2156.99
  5277.3 2152.57  5316.9 2144.99  5335.4 2147.49  5351.3 2147.27  5356.5 2151.82
  5385.7 2150.56  5397.6 2152.92  5418.3 2153.63  5449.5 2157.13  5632.6 2164.04
#Mann= 4 ,-1 , 0
  4534.1     .07       0    4981     .07       0    4985     .07       0
  5177.8    .063       0
#XS Ineff= 2 , 0
                         5184.57         2159.32
Permanent Ineff=
       F       F
Bank Sta=4981,4985
XS Rating Curve= 0 ,0
Exp/Cntr=0.3,0.1

Type RM Length L Ch R = 1 ,4310    ,199,199,199
BEGIN DESCRIPTION:
Salt Branch Trib3 4225
END DESCRIPTION:
XS GIS Cut Line= 3
       1380253.4      6839058.99      1380366.81      6838549.76
      1380583.24       6837805.6
#Sta/Elev= 30
  4478.3 2163.46  4506.8  2161.5  4530.5 2162.25  4653.5 2156.34  4734.5 2154.77
  4739.6 2153.52  4868.6 2149.24  4909.6 2146.39  4930.1 2142.77  4979.3 2141.52
  4979.6 2141.02  4983.3 2141.52  5002.2 2141.88  5053.9 2142.38  5064.3 2143.31
  5081.5 2147.87    5115 2149.11  5153.7 2148.29    5159 2146.28  5187.3 2144.08
  5192.5  2142.3  5210.1 2141.65  5259.5 2143.39  5264.7 2143.62    5283 2150.13
  5314.3  2154.4  5437.6 2160.93  5615.6 2166.85  5703.6 2171.45    5775 2175.72
#Mann= 5 ,-1 , 0
  4478.3    .063       0  4979.3    .063       0  4983.3    .063       0
  5002.2     .07       0  5703.6    .035       0
#XS Ineff= 2 , 0
                         5140.51         2152.76
Permanent Ineff=
       F       F
Bank Sta=4979.3,4983.3
XS Rating Curve= 0 ,0
Exp/Cntr=0.3,0.1

Type RM Length L Ch R = 1 ,4111    ,363,363,363
BEGIN DESCRIPTION:
Salt Branch Trib3 4226
END DESCRIPTION:
XS GIS Cut Line= 3
      1380388.81      6838986.11      1380507.42      6838690.41
      1380746.43      6838197.95
#Sta/Elev= 30
  4681.4 2154.12  4762.7  2151.8  4846.1 2148.09  4899.9 2147.52  4916.4 2146.46
  4924.1  2144.3  4929.5 2140.84    4938 2139.46  4948.3 2140.46  4953.7 2138.29
  4959.5 2137.47  5005.1 2136.56  5005.3 2136.06  5009.1 2136.56  5046.7 2138.26
  5069.2 2140.65  5097.3 2147.27  5136.1 2148.89  5170.6 2151.94  5202.8 2153.25
    5225 2155.07  5255.3 2155.16    5306  2157.3  5368.1 2157.98  5373.7 2159.12
  5435.8 2160.35  5458.4 2162.22  5509.1 2163.18  5514.7 2164.38  5547.4 2165.37
#Mann= 3 ,-1 , 0
  4681.4     .07       0  5005.1     .07       0  5009.1     .07       0
Bank Sta=5005.1,5009.1
XS Rating Curve= 0 ,0
Exp/Cntr=0.3,0.1

Type RM Length L Ch R = 1 ,3748    ,578,578,578
BEGIN DESCRIPTION:
Salt Branch Trib3 4224
END DESCRIPTION:
XS GIS Cut Line= 3
      1380347.17      6839100.68      1380754.13      6838953.36
      1380920.01      6838604.27
#Sta/Elev= 30
  4567.2 2158.69  4660.6 2153.17  4733.2 2150.94  4794.5 2147.48  4886.4 2144.55
  4905.2 2141.61  4911.7 2138.68  4926.5 2135.47  4958.4 2134.28    4971 2133.18
  4971.3 2132.68  4974.8 2132.68    4975 2133.18  4986.6 2133.37  5035.3 2134.44
  5050.2 2135.73    5058 2136.97  5063.6  2140.1  5086.3 2145.39  5094.5 2146.94
  5103.5 2146.84    5109 2148.33  5126.2 2147.48  5160.9 2150.79  5194.2 2150.87
  5245.3 2153.88  5296.3  2154.2  5336.2 2156.25  5358.9 2156.74  5386.5 2156.25
#Mann= 5 ,-1 , 0
  4567.2     .07       0    4971     .07       0    4975     .07       0
  4986.6     .16       0  5103.5     .07       0
Bank Sta=4971,4975
XS Rating Curve= 0 ,0
Exp/Cntr=0.3,0.1

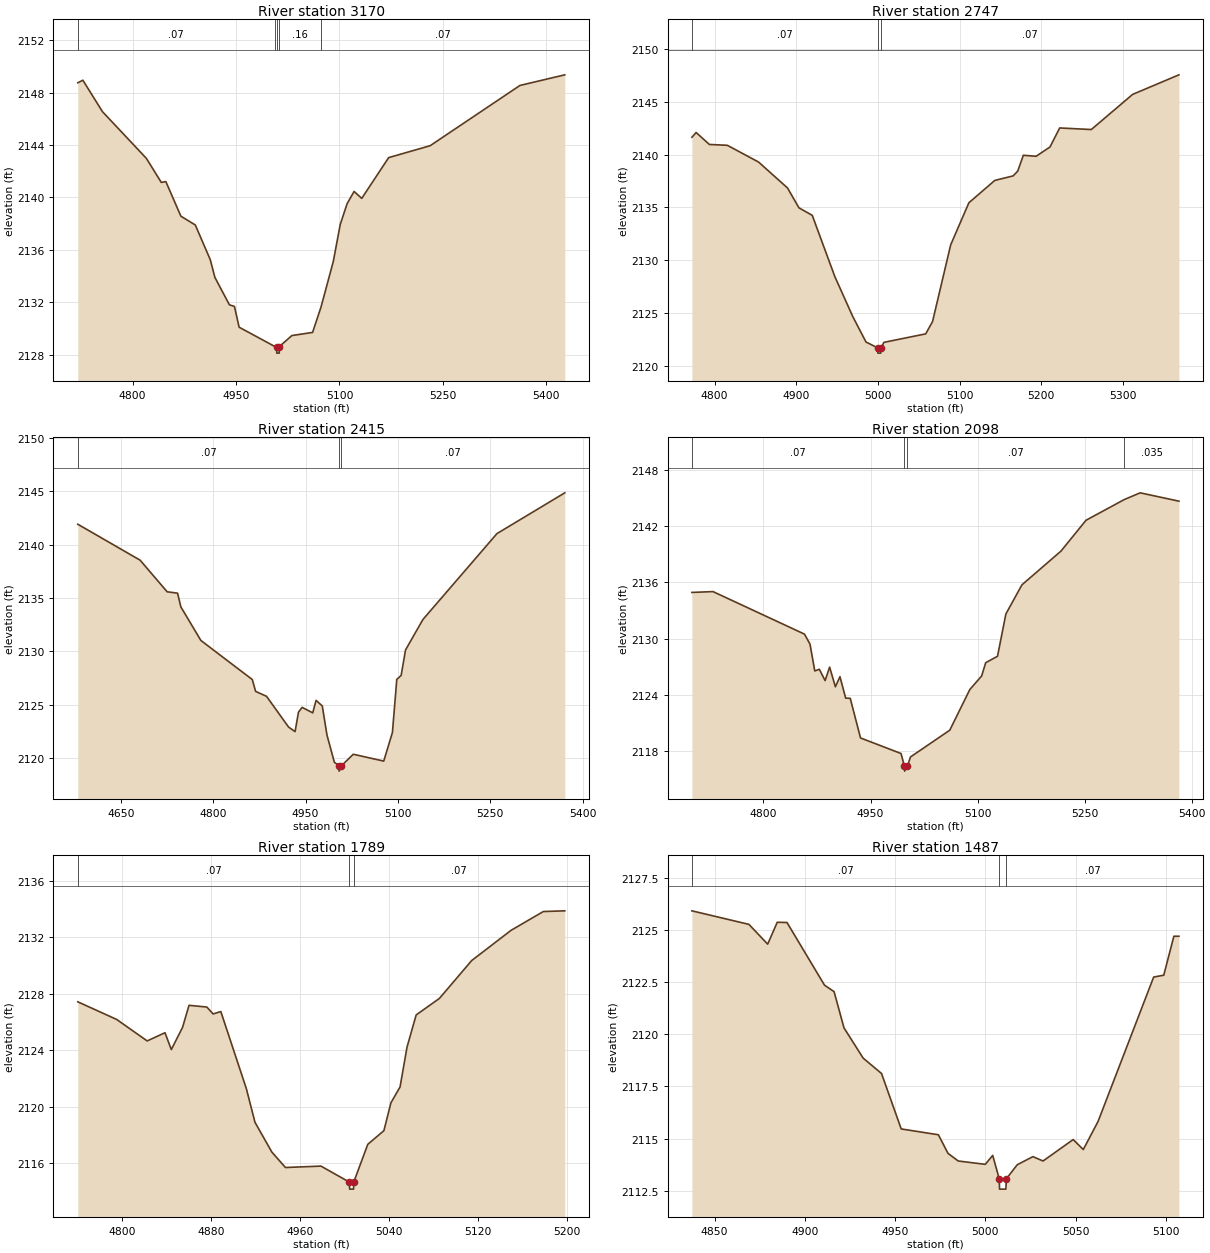
Type RM Length L Ch R = 1 ,3170    ,423,423,423
BEGIN DESCRIPTION:
Salt Branch Trib3 4223
END DESCRIPTION:
XS GIS Cut Line= 3
      1380930.46      6839524.32      1381139.66      6839338.82
      1381107.56      6838913.23
#Sta/Elev= 30
  4720.4 2148.75  4727.8 2148.95  4756.2 2146.55    4820 2142.98  4841.5 2141.15
  4848.2 2141.21    4870 2138.57  4890.9  2137.9  4912.6 2135.25  4919.3  2133.9
  4940.3 2131.81  4947.7 2131.68  4954.4  2130.1  5006.1 2128.63  5008.8 2128.62
  5009.1 2128.12  5012.6 2128.12  5012.8 2128.62  5030.9 2129.46    5061  2129.7
  5073.3 2131.65  5091.1 2135.13  5101.1 2137.94  5111.1 2139.53  5121.2 2140.46
  5132.3 2139.93  5171.3 2143.04  5231.5 2143.95  5361.8 2148.55  5426.8 2149.36
#Mann= 5 ,-1 , 0
  4720.4     .07       0  5006.1     .16       0  5008.8     .07       0
  5012.8     .16       0  5073.3     .07       0
Bank Sta=5008.8,5012.8
XS Rating Curve= 0 ,0
Exp/Cntr=0.3,0.1

Type RM Length L Ch R = 1 ,2747    ,332,332,332
BEGIN DESCRIPTION:
Salt Branch Trib3 4222
END DESCRIPTION:
XS GIS Cut Line= 3
      1381211.73      6839753.46      1381458.25      6839621.52
      1381597.14       6839336.8
#Sta/Elev= 30
  4772.1 2141.63  4777.3 2142.08  4793.5 2140.95  4815.5 2140.87  4853.7 2139.29
  4889.2 2136.84  4903.2 2134.96  4919.5 2134.25  4947.1 2128.47  4969.1 2124.69
  4985.3 2122.28  4999.6 2121.73  4999.8 2121.23  5003.3 2121.23  5003.6 2121.73
  5007.3 2122.25  5058.4 2123.05  5066.8 2124.21    5089 2131.46  5111.3 2135.44
    5143 2137.55  5165.5 2137.98  5171.1 2138.43    5178 2139.93  5193.6 2139.83
  5210.6 2140.71  5222.5 2142.51  5261.2 2142.36  5311.8 2145.68  5368.5 2147.53
#Mann= 3 ,-1 , 0
  4772.1     .07       0  4999.6     .07       0  5003.6     .07       0
Bank Sta=4999.6,5003.6
XS Rating Curve= 0 ,0
Exp/Cntr=0.3,0.1

Type RM Length L Ch R = 1 ,2415    ,317,317,317
BEGIN DESCRIPTION:
Salt Branch Trib3 4221
END DESCRIPTION:
XS GIS Cut Line= 3
      1381232.52      6840069.46      1381615.78      6839897.68
      1381878.36      6839635.44
#Sta/Elev= 30
    4580 2141.92  4681.3 2138.55  4725.2 2135.59  4742.1 2135.46  4747.5 2134.17
    4780 2131.03  4863.5 2127.37  4868.9 2126.26  4886.6  2125.8  4922.4 2122.92
    4933 2122.49  4938.5 2124.31  4944.4 2124.76  4961.7 2124.25  4967.1 2125.42
  4977.2 2124.89  4984.8 2122.17  4996.8 2119.62  5004.3 2119.29  5004.5 2118.79
  5008.3 2119.29  5027.5 2120.37    5077 2119.73  5091.1 2122.41  5098.2 2127.38
  5105.3 2127.76  5112.4 2130.14  5140.6 2132.99  5260.9 2141.04  5371.1 2144.86
#Mann= 3 ,-1 , 0
    4580     .07       0  5004.3     .07       0  5008.3     .07       0
Bank Sta=5004.3,5008.3
XS Rating Curve= 0 ,0
Exp/Cntr=0.3,0.1

Type RM Length L Ch R = 1 ,2098    ,309,309,309
BEGIN DESCRIPTION:
Salt Branch Trib3 4220
END DESCRIPTION:
XS GIS Cut Line= 3
       1381652.7      6840357.62      1381839.35      6840122.37
      1382013.38      6839782.09
#Sta/Elev= 30
  4699.7 2134.92  4729.3 2135.01  4857.5 2130.47  4865.2 2129.41  4871.9 2126.54
  4878.3 2126.72  4886.4 2125.51  4892.7 2126.95  4900.8 2124.85  4907.2 2125.93
  4915.2 2123.64  4921.6 2123.62    4936 2119.39  4992.8 2117.73  4997.6 2116.35
  4997.8 2115.85  5001.6 2116.35    5006 2117.36  5061.1 2120.22  5089.2 2124.56
  5105.8 2126.01  5111.4 2127.42    5128 2128.11  5139.7 2132.62  5162.2 2135.73
  5216.9 2139.33    5252 2142.62  5305.6 2144.83  5327.9 2145.55  5382.2 2144.66
#Mann= 4 ,-1 , 0
  4699.7     .07       0  4997.6     .07       0  5001.6     .07       0
  5305.6    .035       0
Bank Sta=4997.6,5001.6
XS Rating Curve= 0 ,0
Exp/Cntr=0.3,0.1

Type RM Length L Ch R = 1 ,1789    ,302,302,302
BEGIN DESCRIPTION:
Salt Branch Trib3 4.0
END DESCRIPTION:
XS GIS Cut Line= 3
       1381940.9      6840550.09      1382058.33      6840341.35
      1382178.74      6840183.79
#Sta/Elev= 30
  4760.5 2127.43  4795.5 2126.18  4822.9 2124.66  4838.9 2125.24  4844.6 2124.05
  4854.7 2125.62  4860.5 2127.18  4876.5 2127.06  4882.2 2126.57  4889.1 2126.74
  4912.1 2121.27  4919.8  2118.9    4935 2116.79  4947.2  2115.7  4979.1  2115.8
  5004.6 2114.67  5004.9 2114.17  5008.4 2114.17  5008.6 2114.67  5021.2 2117.34
  5035.7 2118.31    5042 2120.28  5050.2  2121.4  5056.5 2124.23  5064.7  2126.5
  5085.6 2127.67  5114.6 2130.35    5150 2132.49    5179 2133.82  5198.3 2133.87
#Mann= 3 ,-1 , 0
  4760.5     .07       0  5004.6     .07       0  5008.6     .07       0
Bank Sta=5004.6,5008.6
XS Rating Curve= 0 ,0
Exp/Cntr=0.3,0.1

Type RM Length L Ch R = 1 ,1487    ,498,498,498
BEGIN DESCRIPTION:
Salt Branch Trib3 3.0
END DESCRIPTION:
XS GIS Cut Line= 3
      1382255.01      6840637.96      1382306.74      6840483.81
      1382355.01      6840387.98
#Sta/Elev= 30
  4837.4 2125.93    4869 2125.28  4879.4 2124.33  4884.7 2125.38  4890.1 2125.37
  4910.9 2122.36  4916.2 2122.05  4921.7 2120.31  4932.3 2118.86  4942.5 2118.12
  4953.4 2115.46    4974 2115.18  4979.3 2114.29    4985 2113.92    5000 2113.76
  5004.1 2114.19  5007.7 2113.07  5007.9 2112.57  5011.4 2112.57  5011.7 2113.07
  5017.7 2113.74  5026.4 2114.13    5032 2113.92  5048.7 2114.95  5054.3 2114.47
  5062.5 2115.82  5093.3 2122.75  5098.9 2122.84  5104.5 2124.71  5107.3 2124.71
#Mann= 3 ,-1 , 0
  4837.4     .07       0  5007.7     .07       0  5011.7     .07       0
Bank Sta=5007.7,5011.7
XS Rating Curve= 0 ,0
Exp/Cntr=0.3,0.1

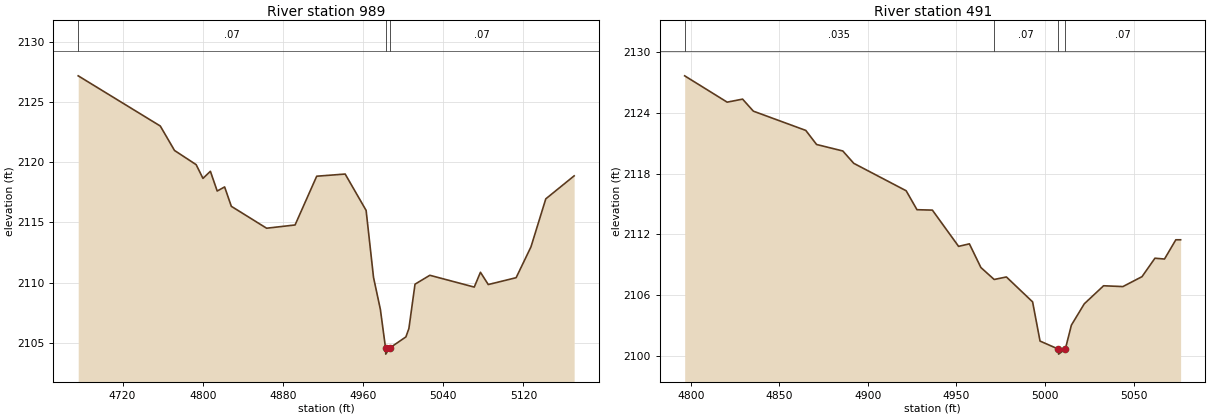
Type RM Length L Ch R = 1 ,989     ,498,498,498
BEGIN DESCRIPTION:
Salt Branch Trib3 2.0
END DESCRIPTION:
XS GIS Cut Line= 3
      1382497.26      6840976.19      1382715.64      6840736.45
      1382854.98      6840638.01
#Sta/Elev= 30
  4675.7 2127.18  4757.6 2123.01  4771.8 2120.98  4793.4  2119.8  4800.2 2118.66
  4807.6 2119.25  4814.4 2117.61  4821.8 2117.95  4828.5 2116.34  4863.7 2114.52
  4892.1 2114.79  4913.7 2118.84  4942.1 2119.02    4963    2116  4970.4 2110.43
  4977.2 2107.79  4982.4 2104.56  4982.6 2104.06  4986.4 2104.56  5002.7 2105.49
  5005.7 2106.19  5011.8 2109.87  5026.6 2110.61  5070.9 2109.63  5077.1 2110.86
  5084.9 2109.84  5112.7 2110.41  5127.5 2112.97  5142.3 2116.96  5170.6 2118.87
#Mann= 3 ,-1 , 0
  4675.7     .07       0  4982.4     .07       0  4986.4     .07       0
Bank Sta=4982.4,4986.4
XS Rating Curve= 0 ,0
Exp/Cntr=0.3,0.1

Type RM Length L Ch R = 1 ,491     ,0,0,0
BEGIN DESCRIPTION:
Salt Branch Trib3 1.0
END DESCRIPTION:
XS GIS Cut Line= 3
       1382907.7      6841174.81      1383024.83       6841008.4
        1383055.      6840937.99
#Sta/Elev= 30
  4796.5 2127.65  4820.5 2125.05  4829.2 2125.35  4835.3 2124.16  4864.9 2122.26
    4871 2120.87  4885.8 2120.23    4892 2119.01  4921.6  2116.3  4927.7 2114.43
  4936.4 2114.39  4951.2 2110.81  4957.3 2111.06  4963.8 2108.72  4971.3 2107.54
  4978.2 2107.79    4993 2105.33  4997.2 2101.46  5007.5 2100.67  5007.7 2100.17
  5011.5 2100.67  5014.9 2103.03  5022.2 2105.14  5033.1 2106.92    5044 2106.84
  5054.8 2107.82  5062.1 2109.64  5067.5 2109.56  5073.9 2111.46  5076.6 2111.46
#Mann= 4 ,-1 , 0
  4796.5    .035       0  4971.3     .07       0  5007.5     .07       0
  5011.5     .07       0
Bank Sta=5007.5,5011.5
XS Rating Curve= 0 ,0
Exp/Cntr=0.3,0.1

Chan Stop Cuts=-1
Use User Specified Reach Order=0
Composite Channel Slope=5