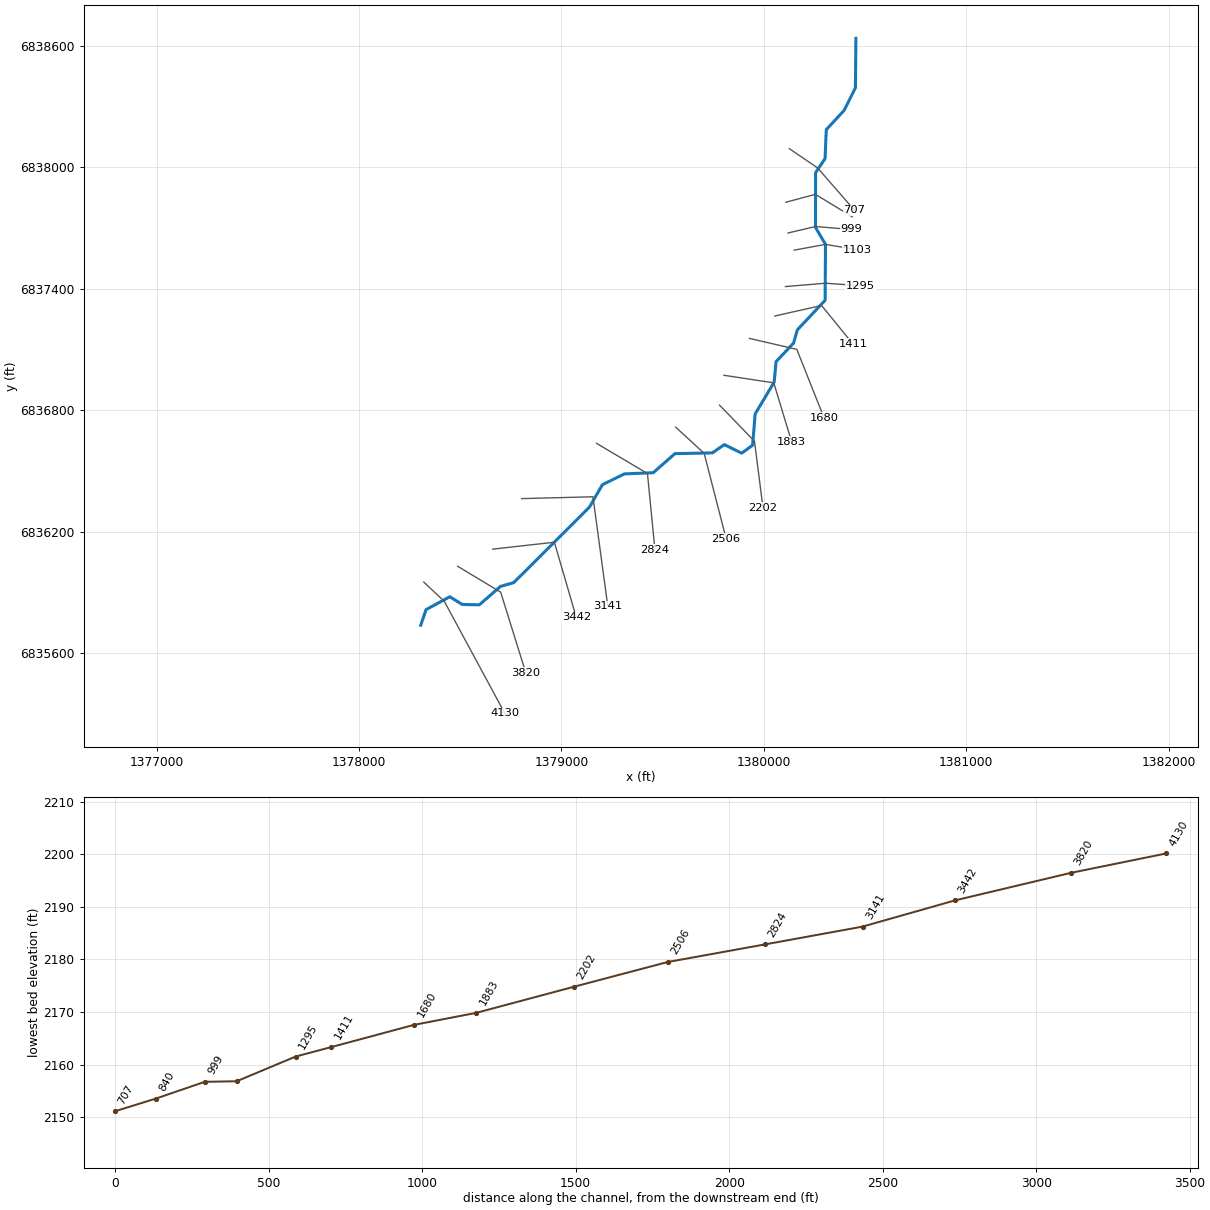
--- Salt Branch Trib3T1.prj (project) ---

Proj Title=Salt Branch Trib3T1 Base Level Engineering
Current Plan=p01
Default Exp/Contr=0.3,0.1
English Units
Geom File=g01
Flow File=f01
Plan File=p01
Y Axis Title=Elevation
X Axis Title(PF)=Main Channel Distance
X Axis Title(XS)=Station
BEGIN DESCRIPTION:
Salt Branch Trib3T1
END DESCRIPTION:
DSS Export Rating Curves= 0
DSS Export Rating Curve Sorted= 0
DSS Export Volume Flow Curves= 0
DXF OffsetX= 0
DXF OffsetY= 0
DXF ScaleX= 1
DXF ScaleY= 10

--- Salt Branch Trib3T1.p01 (plan) ---

Plan Title=Multiple Run
Short Identifier=Multiple
Geom File=g01
Flow File=f01
Subcritical Flow
K Sum by GR= 0
Std Step Tol= 0.01
Critical Tol= 0.01
Num of Std Step Trials= 20
Max Error Tol= 0.3
Flow Tol Ratio= 0.001
Split Flow NTrial= 30
Split Flow Tol= 0.02
Split Flow Ratio= 0.02
Log Output Level= 0
Friction Slope Method= 1
Unsteady Friction Slope Method= 2
Unsteady Bridges Friction Slope Method= 1
Parabolic Critical Depth
Global Vel Dist=  1 , 1 , 1
Global Log Level= 0
CheckData=True
Encroach Param= -1, 0, 0, 0
BEGIN DESCRIPTION:
Multiple Run
END DESCRIPTION:

--- Salt Branch Trib3T1.f01 (steady flow) ---

Flow Title=Multiple
Number of Profiles=7
Profile Names=10-year,25-year,50-year,1pct_min,100-year,1pct_plu,500-year
River Rch & RM= Salt Branch Trib,Reach-1,4130
      71      92     109      64     128     255     178
Boundary for River Rch & Prof#=Salt Branch Trib,Reach-1,1
Up Type=0
Dn Type=3
Dn Slope=0.005
Boundary for River Rch & Prof#=Salt Branch Trib,Reach-1,2
Up Type=0
Dn Type=3
Dn Slope=0.005
Boundary for River Rch & Prof#=Salt Branch Trib,Reach-1,3
Up Type=0
Dn Type=3
Dn Slope=0.005
Boundary for River Rch & Prof#=Salt Branch Trib,Reach-1,4
Up Type=0
Dn Type=3
Dn Slope=0.005
Boundary for River Rch & Prof#=Salt Branch Trib,Reach-1,5
Up Type=0
Dn Type=3
Dn Slope=0.005
Boundary for River Rch & Prof#=Salt Branch Trib,Reach-1,6
Up Type=0
Dn Type=3
Dn Slope=0.005
Boundary for River Rch & Prof#=Salt Branch Trib,Reach-1,7
Up Type=0
Dn Type=3
Dn Slope=0.005

--- Salt Branch Trib3T1.g01 (geometry) ---

Geom Title=Existing Conditions

River Reach=Salt Branch Trib,Reach-1
Reach XY= 30
      1378305.00      6835738.00      1378331.15      6835815.29
      1378448.38      6835878.59      1378510.49      6835840.48
      1378594.51      6835838.95      1378698.96      6835929.82
      1378764.68      6835948.78      1379138.34      6836321.34
      1379202.45      6836432.27      1379310.93      6836485.75
      1379453.53      6836491.56      1379560.86      6836585.93
      1379745.41      6836589.55      1379805.01      6836630.41
      1379891.09      6836588.09      1379944.65      6836627.77
      1379957.25      6836782.07      1380051.17      6836939.59
      1380060.54      6837040.42      1380146.82      6837131.96
      1380165.78      6837197.68      1380302.83      6837343.44
      1380304.79      6837619.73      1380255.52      6837703.22
      1380255.68      6837974.08      1380302.61      6838043.53
      1380308.55      6838186.53      1380396.84      6838281.95
      1380452.65      6838393.52      1380455.00      6838638.00

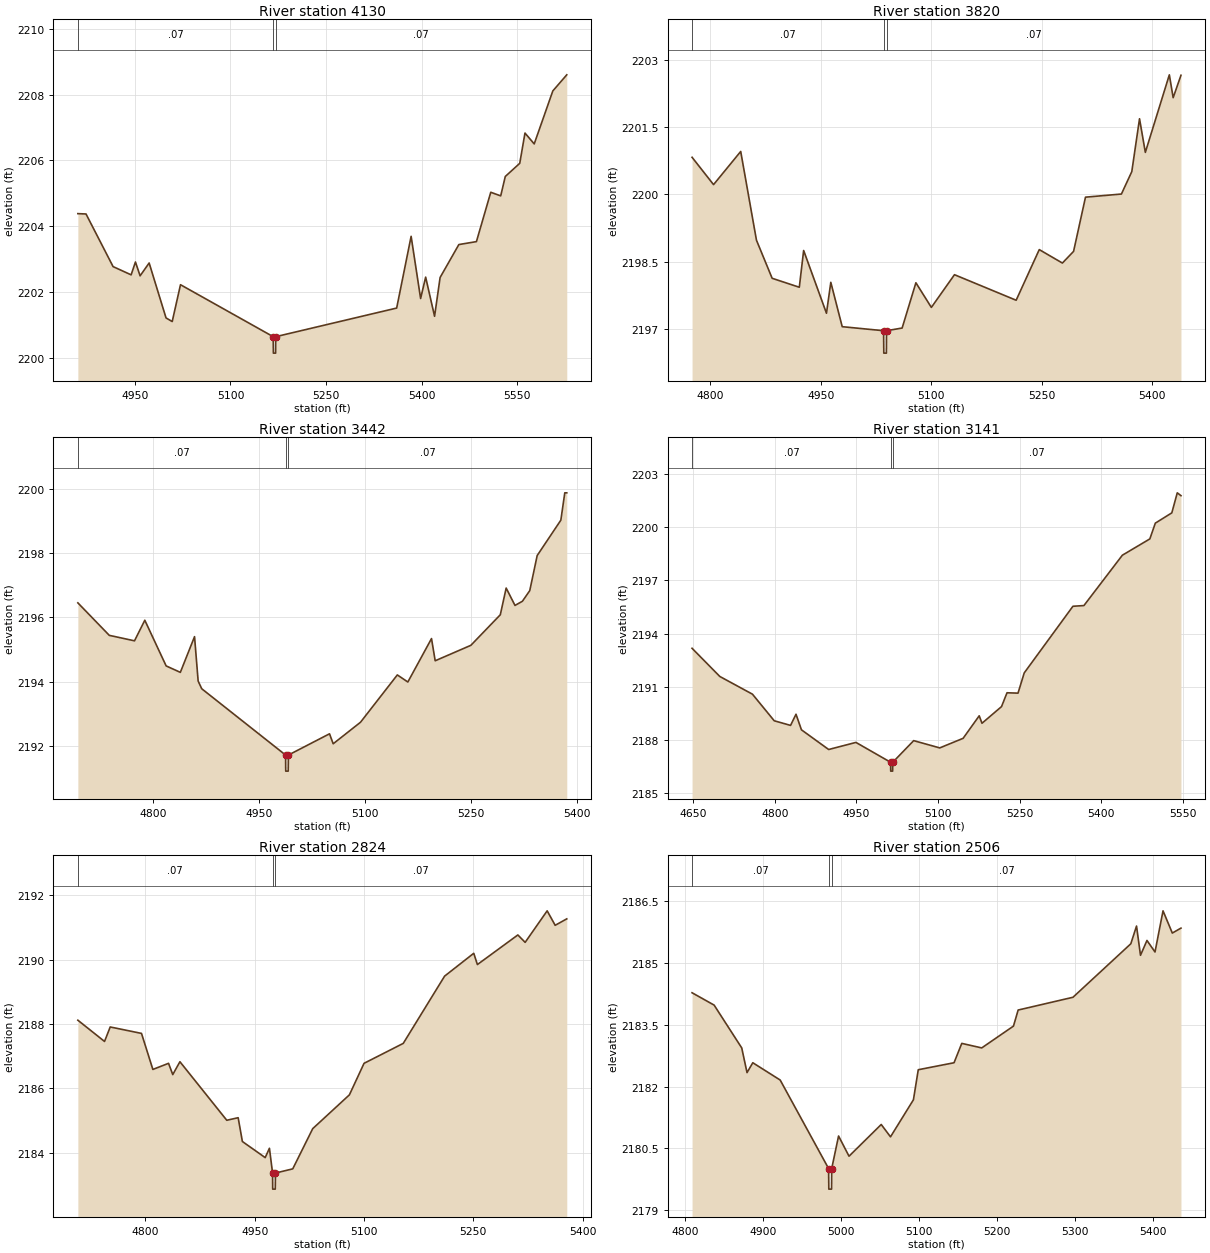
Type RM Length L Ch R = 1,4130,310,310,310
BEGIN DESCRIPTION:
Salt Branch Trib3T1 4256
END DESCRIPTION:
XS GIS Cut Line= 3
      1378320.12      6835951.21      1378421.65      6835855.55
      1378720.02      6835303.06
#Sta/Elev= 30
  4860.5 2204.38  4873.3 2204.37  4915.8 2202.77  4944.1 2202.52  4950.9 2202.91
  4958.2 2202.49  4972.4 2202.88  4998.9 2201.21  5008.6 2201.10  5021.6 2202.22
  5167.1 2200.64  5167.4 2200.14  5170.9 2200.14  5171.1 2200.64  5360.9 2201.51
  5383.6 2203.69  5398.5 2201.80  5406.4 2202.45  5420.4 2201.26  5429.1 2202.44
  5458.5 2203.44  5486.1 2203.53  5508.6 2205.03  5524.2 2204.92  5531.4 2205.51
  5554.1 2205.91  5562.3 2206.83  5576.8 2206.50  5606.0 2208.11  5627.9 2208.60
#Mann=3,-1,0
  4860.5    0.07       0  5167.1    0.07       0  5171.1    0.07       0
Bank Sta=5167.1,5171.1
Exp/Cntr=0.3,0.1

Type RM Length L Ch R = 1,3820,378,378,378
BEGIN DESCRIPTION:
Salt Branch Trib3T1 4255
END DESCRIPTION:
XS GIS Cut Line= 3
      1378487.17      6836029.37      1378699.87      6835901.32
      1378823.56      6835504.20
#Sta/Elev= 30
  4775.0 2200.83  4804.2 2200.22  4841.1 2200.96  4862.5 2198.98  4883.8 2198.13
  4920.7 2197.93  4926.6 2198.75  4957.6 2197.35  4963.5 2198.04  4979.0 2197.05
  5035.2 2196.96  5035.5 2196.46  5039.0 2196.46  5039.2 2196.96  5060.4 2197.02
  5079.1 2198.03  5100.1 2197.48  5131.5 2198.21  5215.3 2197.64  5246.7 2198.77
  5278.1 2198.47  5293.3 2198.73  5309.5 2199.94  5358.3 2200.01  5372.4 2200.51
  5382.9 2201.69  5390.8 2200.94  5423.4 2202.67  5428.6 2202.16  5439.2 2202.66
#Mann=3,-1,0
  4775.0    0.07       0  5035.2    0.07       0  5039.2    0.07       0
Bank Sta=5035.2,5039.2
Exp/Cntr=0.3,0.1

Type RM Length L Ch R = 1,3442,301,301,301
BEGIN DESCRIPTION:
Salt Branch Trib3T1 4254
END DESCRIPTION:
XS GIS Cut Line= 3
      1378660.79      6836113.99      1378965.18      6836148.16
      1379073.12      6835777.67
#Sta/Elev= 30
  4693.7 2196.45  4738.2 2195.44  4773.9 2195.27  4788.5 2195.91  4818.7 2194.49
  4838.8 2194.29  4858.9 2195.40  4864.0 2194.02  4869.1 2193.78  4987.8 2191.72
  4988.0 2191.22  4991.5 2191.22  4991.8 2191.72  5050.0 2192.38  5055.2 2192.07
  5093.9 2192.74  5146.0 2194.21  5160.9 2193.99  5194.4 2195.34  5199.6 2194.65
  5250.1 2195.13  5291.8 2196.08  5300.1 2196.91  5312.6 2196.37  5323.1 2196.50
  5333.5 2196.83  5344.0 2197.92  5377.5 2199.02  5383.1 2199.87  5385.9 2199.87
#Mann=3,-1,0
  4693.7    0.07       0  4987.8    0.07       0  4991.8    0.07       0
Bank Sta=4987.8,4991.8
Exp/Cntr=0.3,0.1

Type RM Length L Ch R = 1,3141,317,317,317
BEGIN DESCRIPTION:
Salt Branch Trib3T1 4253
END DESCRIPTION:
XS GIS Cut Line= 3
      1378804.04      6836363.56      1379155.82      6836372.76
      1379229.16      6835831.31
#Sta/Elev= 30
  4648.1 2193.17  4699.1 2191.58  4759.1 2190.58  4799.1 2189.08  4829.1 2188.82
  4839.1 2189.45  4849.1 2188.57  4899.1 2187.46  4949.2 2187.86  5012.9 2186.74
  5013.1 2186.24  5016.6 2186.24  5016.9 2186.74  5055.3 2187.96  5103.2 2187.55
  5146.1 2188.09  5175.7 2189.36  5180.8 2188.94  5216.7 2189.88  5226.8 2190.66
  5247.0 2190.64  5258.4 2191.78  5347.9 2195.54  5368.1 2195.58  5438.7 2198.42
  5489.2 2199.34  5499.3 2200.23  5529.6 2200.81  5539.6 2201.94  5546.4 2201.78
#Mann=3,-1,0
  4648.1    0.07       0  5012.9    0.07       0  5016.9    0.07       0
Bank Sta=5012.9,5016.9
Exp/Cntr=0.3,0.1

Type RM Length L Ch R = 1,2824,318,318,318
BEGIN DESCRIPTION:
Salt Branch Trib3T1 4252
END DESCRIPTION:
XS GIS Cut Line= 3
      1379173.50      6836636.67      1379425.16      6836487.60
      1379461.95      6836111.20
#Sta/Elev= 30
  4707.5 2188.12  4744.1 2187.46  4751.9 2187.91  4794.8 2187.71  4810.4 2186.59
  4831.9 2186.78  4837.7 2186.43  4847.5 2186.83  4911.8 2185.01  4927.4 2185.09
  4933.2 2184.35  4964.5 2183.85  4970.3 2184.14  4974.6 2183.37  4974.8 2182.87
  4978.3 2182.87  4978.6 2183.37  5002.3 2183.50  5029.7 2184.75  5080.0 2185.80
  5100.1 2186.78  5153.9 2187.40  5210.6 2189.49  5250.6 2190.20  5255.6 2189.85
  5311.1 2190.77  5321.1 2190.54  5351.3 2191.52  5362.3 2191.07  5378.2 2191.27
#Mann=3,-1,0
  4707.5    0.07       0  4974.6    0.07       0  4978.6    0.07       0
Bank Sta=4974.6,4978.6
Exp/Cntr=0.3,0.1

Type RM Length L Ch R = 1,2506,304,304,304
BEGIN DESCRIPTION:
Salt Branch Trib3T1 4251
END DESCRIPTION:
XS GIS Cut Line= 3
      1379564.11      6836716.98      1379705.18      6836587.63
      1379813.69      6836165.76
#Sta/Elev= 30
  4808.6 2184.28  4836.9 2183.98  4872.3 2182.94  4879.1 2182.34  4886.5 2182.58
  4921.6 2182.16  4983.7 2180.01  4984.0 2179.51  4987.5 2179.51  4987.7 2180.01
  4996.5 2180.80  5009.9 2180.31  5051.2 2181.08  5063.1 2180.78  5092.5 2181.68
  5098.7 2182.41  5144.6 2182.58  5154.5 2183.05  5180.1 2182.94  5220.8 2183.47
  5226.8 2183.86  5297.1 2184.17  5371.3 2185.47  5378.6 2185.90  5383.7 2185.19
  5392.0 2185.55  5402.3 2185.27  5412.6 2186.27  5424.5 2185.73  5435.6 2185.85
#Mann=3,-1,0
  4808.6    0.07       0  4983.7    0.07       0  4987.7    0.07       0
Bank Sta=4983.7,4987.7
Exp/Cntr=0.3,0.1

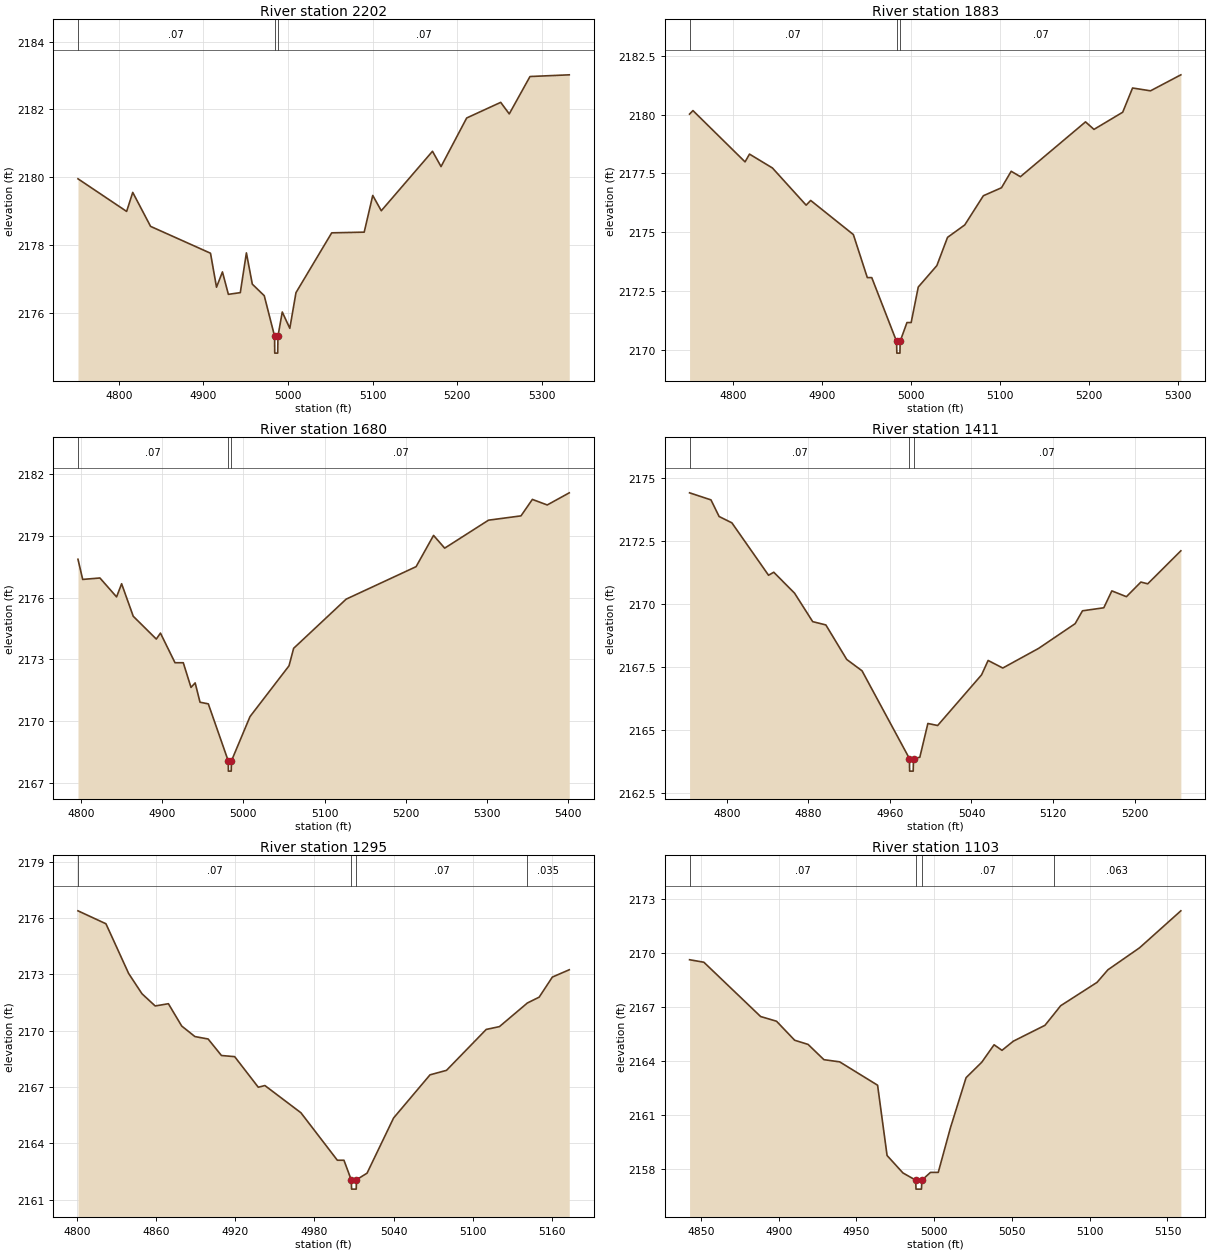
Type RM Length L Ch R = 1,2202,319,319,319
BEGIN DESCRIPTION:
Salt Branch Trib3T1 4250
END DESCRIPTION:
XS GIS Cut Line= 3
      1379781.12      6836825.49      1379953.85      6836647.40
      1379995.98      6836317.68
#Sta/Elev= 30
  4751.9 2179.96  4809.4 2179.00  4816.6 2179.56  4837.7 2178.56  4908.5 2177.77
  4915.6 2176.77  4922.6 2177.22  4929.6 2176.56  4943.7 2176.61  4950.9 2177.78
  4957.9 2176.86  4972.0 2176.52  4984.2 2175.33  4984.4 2174.83  4987.9 2174.83
  4988.2 2175.33  4993.3 2176.04  5002.2 2175.56  5009.5 2176.61  5051.7 2178.37
  5090.1 2178.39  5100.2 2179.47  5110.3 2179.02  5170.8 2180.77  5180.9 2180.32
  5211.2 2181.75  5251.4 2182.21  5261.5 2181.87  5286.0 2182.97  5332.4 2183.02
#Mann=3,-1,0
  4751.9    0.07       0  4984.2    0.07       0  4988.2    0.07       0
Bank Sta=4984.2,4988.2
Exp/Cntr=0.3,0.1

Type RM Length L Ch R = 1,1883,203,203,203
BEGIN DESCRIPTION:
Salt Branch Trib3T1 4249
END DESCRIPTION:
XS GIS Cut Line= 3
      1379802.84      6836973.04      1380049.23      6836935.68
      1380137.04      6836645.37
#Sta/Elev= 30
  4750.8 2180.02  4754.6 2180.17  4813.2 2177.99  4818.2 2178.32  4844.0 2177.73
  4881.9 2176.15  4887.0 2176.35  4935.0 2174.90  4950.7 2173.07  4955.7 2173.07
  4983.6 2170.36  4983.9 2169.86  4987.4 2169.86  4987.6 2170.36  4995.3 2171.16
  5000.0 2171.16  5008.0 2172.67  5028.9 2173.58  5040.9 2174.78  5060.3 2175.31
  5081.2 2176.55  5101.6 2176.89  5112.5 2177.59  5122.9 2177.36  5196.1 2179.69
  5205.6 2179.37  5237.9 2180.10  5249.0 2181.13  5269.2 2181.01  5303.3 2181.69
#Mann=3,-1,0
  4750.8    0.07       0  4983.6    0.07       0  4987.6    0.07       0
Bank Sta=4983.6,4987.6
Exp/Cntr=0.3,0.1

Type RM Length L Ch R = 1,1680,269,269,269
BEGIN DESCRIPTION:
Salt Branch Trib3T1 4248
END DESCRIPTION:
XS GIS Cut Line= 3
      1379928.72      6837155.33      1380163.08      6837101.08
      1380297.54      6836762.78
#Sta/Elev= 30
  4796.6 2177.87  4802.4 2176.89  4823.6 2176.96  4844.1 2176.04  4850.3 2176.68
  4864.6 2175.10  4893.0 2173.99  4898.1 2174.28  4916.0 2172.84  4926.2 2172.84
  4935.7 2171.64  4940.8 2171.86  4946.8 2170.92  4957.0 2170.84  4981.5 2168.07
  4981.7 2167.57  4985.2 2167.57  4985.5 2168.07  5008.3 2170.22  5056.3 2172.69
  5062.0 2173.54  5126.6 2175.93  5212.7 2177.51  5234.2 2179.03  5247.9 2178.41
  5301.8 2179.77  5341.8 2179.98  5355.8 2180.78  5374.1 2180.51  5401.2 2181.10
#Mann=3,-1,0
  4796.6    0.07       0  4981.5    0.07       0  4985.5    0.07       0
Bank Sta=4981.5,4985.5
Exp/Cntr=0.3,0.1

Type RM Length L Ch R = 1,1411,116,116,116
BEGIN DESCRIPTION:
Salt Branch Trib3T1 4247
END DESCRIPTION:
XS GIS Cut Line= 3
      1380054.54      6837266.00      1380285.39      6837317.84
      1380440.45      6837127.63
#Sta/Elev= 30
  4763.4 2174.40  4784.4 2174.12  4792.4 2173.46  4804.9 2173.21  4840.9 2171.13
  4846.0 2171.25  4866.4 2170.42  4884.2 2169.29  4897.1 2169.16  4917.6 2167.79
  4932.6 2167.34  4979.1 2163.86  4979.3 2163.36  4982.8 2163.36  4983.1 2163.86
  4989.3 2163.91  4997.2 2165.25  5006.8 2165.17  5049.9 2167.18  5056.3 2167.75
  5070.7 2167.45  5105.9 2168.23  5141.7 2169.21  5148.9 2169.72  5169.8 2169.84
  5177.7 2170.51  5192.0 2170.28  5206.2 2170.86  5212.9 2170.79  5245.4 2172.10
#Mann=3,-1,0
  4763.4    0.07       0  4979.1    0.07       0  4983.1    0.07       0
Bank Sta=4979.1,4983.1
Exp/Cntr=0.3,0.1

Type RM Length L Ch R = 1,1295,192,192,192
BEGIN DESCRIPTION:
Salt Branch Trib3T1 4246
END DESCRIPTION:
XS GIS Cut Line= 3
      1380106.71      6837411.41      1380305.12      6837427.95
      1380477.79      6837415.75
#Sta/Elev= 30
  4800.9 2176.39  4822.1 2175.70  4839.3 2173.05  4849.4 2171.97  4859.4 2171.32
  4869.4 2171.44  4879.5 2170.25  4889.5 2169.69  4899.5 2169.56  4909.6 2168.68
  4919.6 2168.62  4937.5 2166.99  4942.5 2167.08  4969.8 2165.63  4997.4 2163.10
  5002.4 2163.10  5007.9 2162.06  5008.2 2161.56  5011.7 2161.56  5011.9 2162.06
  5019.9 2162.41  5040.0 2165.35  5067.6 2167.65  5080.1 2167.89  5110.2 2170.07
  5120.2 2170.22  5141.4 2171.48  5150.3 2171.79  5160.3 2172.86  5173.1 2173.25
#Mann=4,-1,0
  4800.9    0.07       0  5007.9    0.07       0  5011.9    0.07       0
  5141.4   0.035       0
Bank Sta=5007.9,5011.9
Exp/Cntr=0.3,0.1

Type RM Length L Ch R = 1,1103,104,104,104
BEGIN DESCRIPTION:
Salt Branch Trib3T1 4245
END DESCRIPTION:
XS GIS Cut Line= 3
      1380150.04      6837591.53      1380304.79      6837619.73
      1380461.27      6837593.91
#Sta/Elev= 30
  4842.7 2169.63  4851.9 2169.49  4888.4 2166.47  4898.6 2166.21  4910.3 2165.15
  4918.9 2164.92  4929.1 2164.07  4939.2 2163.95  4963.6 2162.65  4969.7 2158.74
  4979.9 2157.77  4988.1 2157.37  4988.3 2156.87  4991.8 2156.87  4992.1 2157.37
  4997.6 2157.80  5002.6 2157.80  5010.4 2160.27  5020.5 2163.07  5030.6 2163.93
  5038.5 2164.90  5043.6 2164.59  5050.9 2165.10  5071.2 2165.98  5076.8 2166.58
  5081.3 2167.07  5104.7 2168.37  5111.7 2169.07  5132.0 2170.29  5158.6 2172.35
#Mann=4,-1,0
  4842.7    0.07       0  4988.1    0.07       0  4992.1    0.07       0
  5076.8   0.063       0
Bank Sta=4988.1,4992.1
Exp/Cntr=0.3,0.1

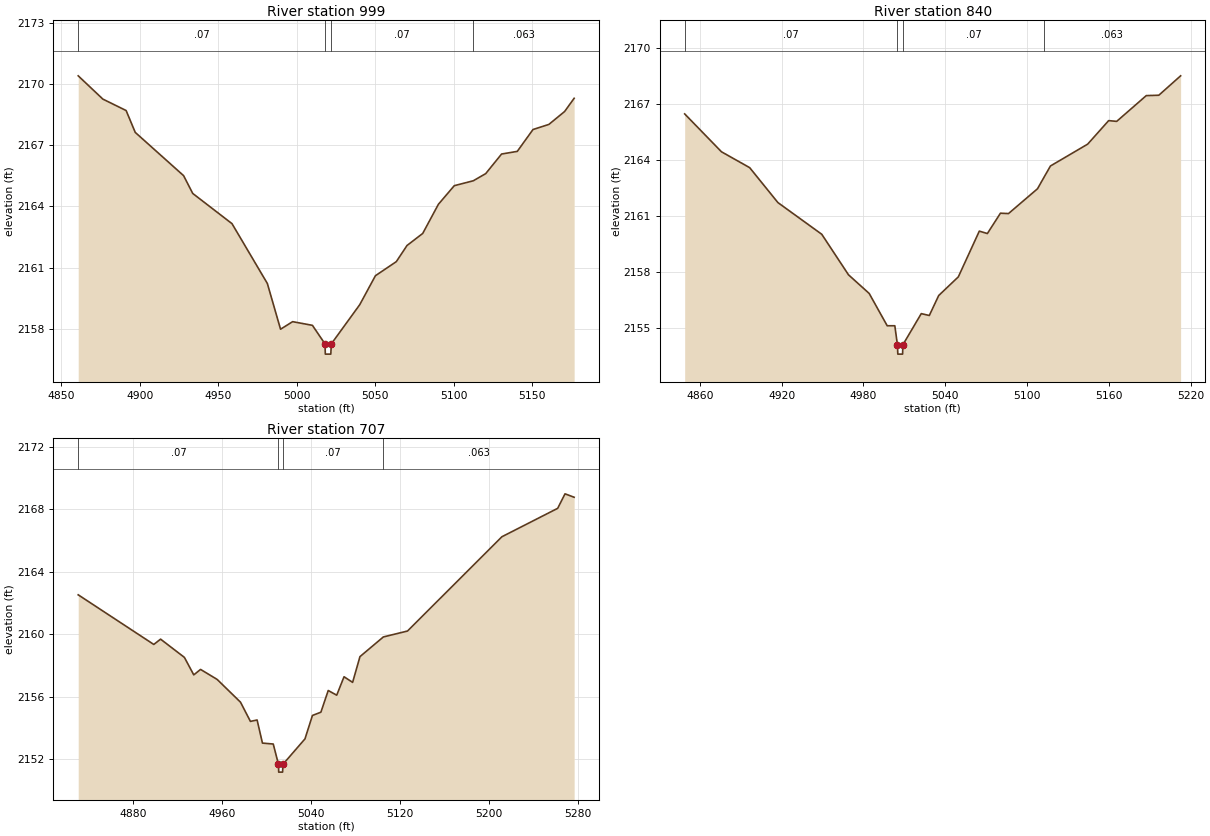
Type RM Length L Ch R = 1,999,159,159,159
BEGIN DESCRIPTION:
Salt Branch Trib3T1 4244
END DESCRIPTION:
XS GIS Cut Line= 3
      1380119.67      6837676.16      1380255.07      6837708.03
      1380431.08      6837693.62
#Sta/Elev= 30
  4860.9 2170.39  4876.6 2169.25  4891.4 2168.69  4897.2 2167.62  4928.0 2165.50
  4933.8 2164.63  4958.8 2163.15  4981.3 2160.22  4989.7 2157.98  4997.4 2158.35
  5010.0 2158.17  5018.0 2157.26  5018.2 2156.76  5021.7 2156.76  5022.0 2157.26
  5040.1 2159.18  5050.1 2160.60  5063.4 2161.29  5070.2 2162.08  5080.2 2162.67
  5090.2 2164.10  5100.3 2165.01  5112.4 2165.25  5120.3 2165.60  5130.4 2166.56
  5140.4 2166.69  5150.4 2167.76  5160.5 2168.01  5170.5 2168.64  5176.6 2169.29
#Mann=4,-1,0
  4860.9    0.07       0  5018.0    0.07       0  5022.0    0.07       0
  5112.4   0.063       0
Bank Sta=5018,5022
Exp/Cntr=0.3,0.1

Type RM Length L Ch R = 1,840,133,133,133
BEGIN DESCRIPTION:
Salt Branch Trib3T1 4243
END DESCRIPTION:
XS GIS Cut Line= 3
      1380108.88      6837828.09      1380254.94      6837867.15
      1380436.56      6837756.44
#Sta/Elev= 30
  4848.8 2166.45  4875.8 2164.42  4896.5 2163.57  4917.2 2161.70  4949.4 2160.00
  4969.0 2157.83  4984.2 2156.83  4997.4 2155.10  5003.0 2155.10  5004.9 2154.08
  5005.2 2153.58  5008.7 2153.58  5008.9 2154.08  5022.4 2155.75  5028.3 2155.65
  5035.2 2156.72  5049.6 2157.72  5065.0 2160.17  5070.9 2160.04  5080.5 2161.13
  5086.4 2161.11  5107.7 2162.44  5112.5 2163.06  5117.2 2163.66  5144.5 2164.83
  5159.9 2166.09  5165.8 2166.05  5187.5 2167.43  5196.7 2167.45  5212.7 2168.49
#Mann=4,-1,0
  4848.8    0.07       0  5004.9    0.07       0  5008.9    0.07       0
  5112.5   0.063       0
Bank Sta=5004.9,5008.9
Exp/Cntr=0.3,0.1

Type RM Length L Ch R = 1,707,0,0,0
BEGIN DESCRIPTION:
Salt Branch Trib3T1 4242
END DESCRIPTION:
XS GIS Cut Line= 3
      1380126.20      6838092.83      1380265.85      6837997.65
      1380447.34      6837789.05
#Sta/Elev= 30
  4831.0 2162.53  4898.9 2159.35  4905.0 2159.69  4926.4 2158.52  4934.8 2157.40
  4940.9 2157.75  4955.8 2157.11  4976.8 2155.65  4985.7 2154.42  4991.7 2154.51
  4996.5 2153.03  5006.2 2152.97  5010.9 2151.67  5011.1 2151.17  5014.6 2151.17
  5014.9 2151.67  5034.7 2153.30  5041.4 2154.80  5049.0 2155.01  5055.6 2156.40
  5063.2 2156.10  5069.8 2157.28  5077.5 2156.92  5084.1 2158.57  5105.1 2159.83
  5126.8 2160.21  5211.6 2166.25  5261.7 2168.07  5268.3 2169.00  5276.5 2168.78
#Mann=4,-1,0
  4831.0    0.07       0  5010.9    0.07       0  5014.9    0.07       0
  5105.1   0.063       0
Bank Sta=5010.9,5014.9
Exp/Cntr=0.3,0.1

Chan Stop Cuts=-1