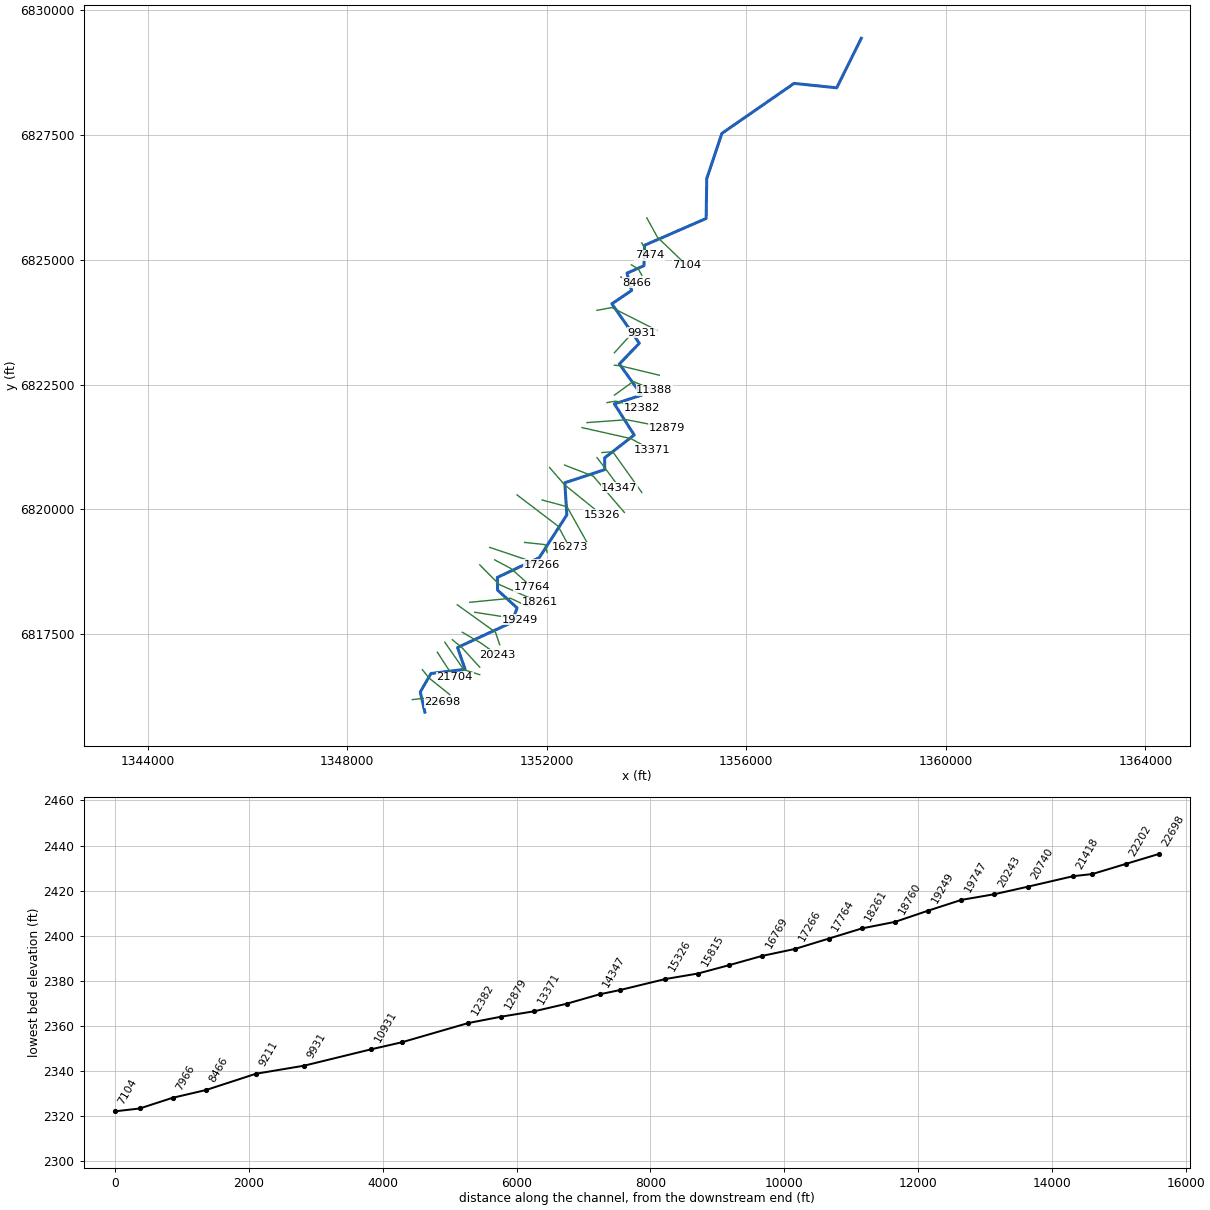
--- Seale Creek.prj (project) ---

Proj Title=Seale Creek Base Level Engineering
Current Plan=p01
Default Exp/Contr=0.3,0.1
English Units
Geom File=g01
Flow File=f01
Plan File=p01
Y Axis Title=Elevation
X Axis Title(PF)=Main Channel Distance
X Axis Title(XS)=Station
BEGIN DESCRIPTION:
Seale Creek
END DESCRIPTION:
DSS Export Rating Curves= 0
DSS Export Rating Curve Sorted= 0
DSS Export Volume Flow Curves= 0
DXF OffsetX= 0
DXF OffsetY= 0
DXF ScaleX= 1
DXF ScaleY= 10

--- Seale Creek.p01 (plan) ---

Plan Title=Multiple Run
Short Identifier=Multiple
Geom File=g01
Flow File=f01
Subcritical Flow
K Sum by GR= 0
Std Step Tol= 0.01
Critical Tol= 0.01
Num of Std Step Trials= 20
Max Error Tol= 0.3
Flow Tol Ratio= 0.001
Split Flow NTrial= 30
Split Flow Tol= 0.02
Split Flow Ratio= 0.02
Log Output Level= 0
Friction Slope Method= 1
Unsteady Friction Slope Method= 2
Unsteady Bridges Friction Slope Method= 1
Parabolic Critical Depth
Global Vel Dist=  1 , 1 , 1
Global Log Level= 0
CheckData=True
Encroach Param= -1, 0, 0, 0
BEGIN DESCRIPTION:
Multiple Run
END DESCRIPTION:

--- Seale Creek.f01 (steady flow) ---

Flow Title=Multiple
Number of Profiles=7
Profile Names=10-year,25-year,50-year,1pct_min,100-year,1pct_plu,500-year
River Rch & RM= Seale Creek,Reach-1,22698
     453     660     839     530    1057    2109    1701
River Rch & RM= Seale Creek,Reach-1,14645
     556     819    1049     666    1329    2652    2166
River Rch & RM= Seale Creek,Reach-1,13371
     631     934    1199     763    1523    3039    2493
River Rch & RM= Seale Creek,Reach-1,7474
     843    1271    1651    1063    2121    4232    3551
River Rch & RM= Seale Creek,Reach-1,3350
     910    1376    1791    1155    2304    4596    3869
Boundary for River Rch & Prof#=Seale Creek,Reach-1,1
Up Type=0
Dn Type=3
Dn Slope=0.005
Boundary for River Rch & Prof#=Seale Creek,Reach-1,2
Up Type=0
Dn Type=3
Dn Slope=0.005
Boundary for River Rch & Prof#=Seale Creek,Reach-1,3
Up Type=0
Dn Type=3
Dn Slope=0.005
Boundary for River Rch & Prof#=Seale Creek,Reach-1,4
Up Type=0
Dn Type=3
Dn Slope=0.005
Boundary for River Rch & Prof#=Seale Creek,Reach-1,5
Up Type=0
Dn Type=3
Dn Slope=0.005
Boundary for River Rch & Prof#=Seale Creek,Reach-1,6
Up Type=0
Dn Type=3
Dn Slope=0.005
Boundary for River Rch & Prof#=Seale Creek,Reach-1,7
Up Type=0
Dn Type=3
Dn Slope=0.005

--- Seale Creek.g01 (geometry) ---

Geom Title=Existing Conditions
Program Version=4.10

River Reach=Seale Creek     ,Reach-1
Reach XY= 30
        1349555.        6815938.      1349462.78       6816341.4
      1349677.81      6816711.97      1350361.57      6816795.69
      1350210.02      6817232.91      1351299.17       6817735.7
      1351403.47      6818026.12      1351012.26       6818381.9
      1351008.46      6818636.51      1351847.27       6819031.5
      1352401.46      6819889.46      1352360.17      6820532.59
      1353161.09      6820796.14      1353159.74      6821032.38
      1353751.45      6821489.47      1353354.45      6822113.12
      1353901.63      6822289.22      1353454.64       6822912.8
      1353854.07      6823327.51      1353304.92      6824118.12
      1353699.55      6824385.55      1353606.87      6824732.31
      1353947.31      6824881.52      1353960.15      6825290.89
       1355193.9      6825827.94       1355206.2       6826627.5
      1355510.11      6827532.89      1356956.55      6828534.25
      1357811.19      6828445.75        1358305.        6829438.

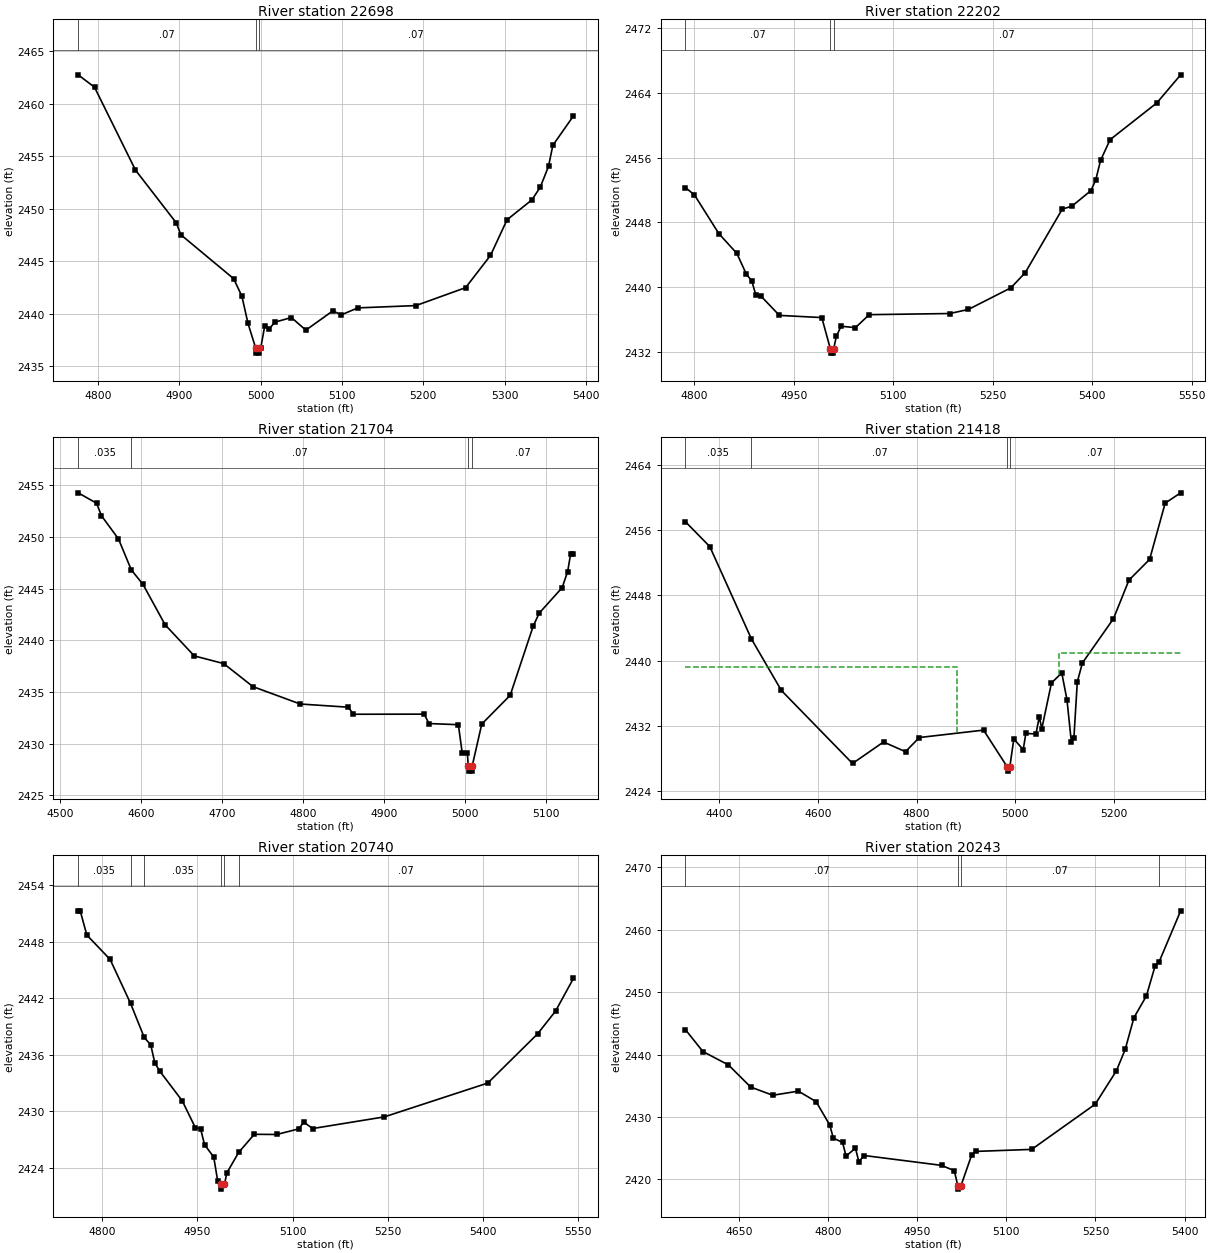
Type RM Length L Ch R = 1 ,22698   ,496,496,496
BEGIN DESCRIPTION:
Seale Creek 41.0
END DESCRIPTION:
XS GIS Cut Line= 3
      1349305.04        6816188.      1349528.06      6816214.56
      1349904.97      6816138.01
#Sta/Elev= 30
  4775.4 2462.77  4795.5 2461.59  4845.9 2453.69  4896.2 2448.65  4901.7 2447.53
  4966.7 2443.34  4976.8 2441.67  4984.3 2439.08  4993.7 2436.75    4994 2436.25
  4997.8 2436.25  4998.1 2436.75    5000 2436.75  5004.9 2438.85    5010 2438.52
  5017.3  2439.2  5037.7 2439.64  5055.5 2438.44  5088.7 2440.28  5098.9 2439.89
  5119.3 2440.56  5190.8 2440.78    5252 2442.49  5282.6 2445.56    5303 2448.96
  5333.6 2450.86  5343.8 2452.06    5354 2454.05  5359.3 2456.05  5384.6 2458.85
#Mann= 3 ,-1 , 0
  4775.4     .07       0  4993.7     .07       0  4998.1     .07       0
Bank Sta=4993.7,4998.1
XS Rating Curve= 0 ,0
Exp/Cntr=0.3,0.1

Type RM Length L Ch R = 1 ,22202   ,498,498,498
BEGIN DESCRIPTION:
Seale Creek 40.0
END DESCRIPTION:
XS GIS Cut Line= 3
        1349505.      6816787.99      1349638.31      6816621.35
      1350054.98      6816288.02
#Sta/Elev= 30
  4786.6 2452.31  4800.2  2451.4    4837 2446.61  4864.2 2444.16  4878.6 2441.57
  4886.6 2440.78    4893 2438.96  4901.1 2438.83  4928.3 2436.49  4992.3 2436.22
  5005.3 2432.32  5005.7 2431.82  5009.8 2431.82  5010.2 2432.32  5014.2  2433.9
  5021.4 2435.15    5043 2434.97  5063.8 2436.58  5185.5 2436.72  5213.5 2437.23
  5277.5  2439.9  5299.1 2441.77  5355.1 2449.65  5369.5    2450  5398.4 2451.94
  5405.6 2453.28  5412.8 2455.67  5427.2 2458.24  5497.6 2462.78  5533.6 2466.26
#Mann= 3 ,-1 , 0
  4786.6     .07       0  5005.3     .07       0  5010.2     .07       0
Bank Sta=5005.3,5010.2
XS Rating Curve= 0 ,0
Exp/Cntr=0.3,0.1

Type RM Length L Ch R = 1 ,21704   ,286,286,286
BEGIN DESCRIPTION:
Seale Creek 39.0
END DESCRIPTION:
XS GIS Cut Line= 3
      1349804.97      6817138.04      1350065.19      6816737.55
      1350155.02      6816637.98
#Sta/Elev= 30
  4522.4 2454.26  4545.2 2453.25  4551.1 2452.05  4572.2  2449.8    4588 2446.81
  4602.5  2445.4  4629.8  2441.5  4665.8 2438.49  4702.1 2437.75  4738.3 2435.52
  4796.7 2433.84  4856.2 2433.53  4862.2 2432.85  4949.8 2432.86  4955.7 2431.95
    4992 2431.84  4996.7 2429.14  5003.1 2429.14  5004.2 2427.85  5004.6 2427.35
  5008.8 2427.35  5009.1 2427.85  5020.9  2431.9    5056 2434.68  5084.4 2441.36
  5091.8 2442.62  5120.2 2445.09    5127 2446.65  5130.7 2448.37  5134.1 2448.37
#Mann= 4 ,-1 , 0
  4522.4    .035       0    4588     .07       0  5004.2     .07       0
  5009.1     .07       0
Bank Sta=5004.2,5009.1
XS Rating Curve= 0 ,0
Exp/Cntr=0.3,0.1

Type RM Length L Ch R = 1 ,21418   ,678,678,678
BEGIN DESCRIPTION:
Seale Creek 38.0
END DESCRIPTION:
XS GIS Cut Line= 3
      1349954.98      6817338.04      1350335.14      6816787.92
        1350655.        6816688.
#Sta/Elev= 30
  4331.3 2457.06  4380.7    2454  4465.1 2442.65  4525.8 2436.32    4670 2427.35
  4732.8 2429.99  4777.4  2428.8  4805.4 2430.54  4935.6 2431.45  4983.8 2426.91
  4984.2 2426.41  4988.8 2426.91  4996.9 2430.36    5016 2429.05  5021.3 2431.04
  5041.8 2430.98  5048.5 2433.08  5053.7 2431.64  5073.2 2437.24  5094.1 2438.48
  5104.6 2435.21  5113.5 2430.02  5118.7 2430.47  5125.6 2437.38    5136 2439.71
  5198.9 2445.14  5230.3 2449.88  5272.2 2452.43  5303.7 2459.34  5335.1 2460.61
#Mann= 4 ,-1 , 0
  4331.3    .035       0  4465.1     .07       0  4983.8     .07       0
  4988.8     .07       0
#XS Ineff= 2 , 0
         4882.23 2439.24 5089.34         2440.97
Permanent Ineff=
       F       F
Bank Sta=4983.8,4988.8
XS Rating Curve= 0 ,0
Exp/Cntr=0.3,0.1

Type RM Length L Ch R = 1 ,20740   ,497,497,497
BEGIN DESCRIPTION:
Seale Creek 37.0
END DESCRIPTION:
XS GIS Cut Line= 3
      1350105.01      6817387.99      1350289.64      6817238.59
      1350655.01      6816837.99
#Sta/Elev= 30
  4762.5 2451.28  4765.7 2451.28  4776.1 2448.71  4812.8 2446.12    4845 2441.45
  4866.5 2437.84  4876.8 2437.04  4883.2 2435.12  4891.1 2434.25  4926.3 2431.12
  4947.2 2428.23  4955.1 2428.17  4961.5 2426.45  4975.9 2425.15  4982.3 2422.55
  4987.8 2422.24  4988.1 2421.74  4992.8 2422.24  4996.5 2423.45  5015.1 2425.63
  5039.8 2427.56    5075 2427.54  5110.1 2428.14  5117.5 2428.86  5131.7 2428.17
  5244.6 2429.41  5407.4    2433  5485.8 2438.22  5514.1 2440.64  5542.2  2444.1
#Mann= 6 ,-1 , 0
  4762.5    .035       0    4845     .07       0  4866.5    .035       0
  4987.8    .035       0  4992.8    .035       0  5015.1     .07       0
Bank Sta=4987.8,4992.8
XS Rating Curve= 0 ,0
Exp/Cntr=0.3,0.1

Type RM Length L Ch R = 1 ,20243   ,496,496,496
BEGIN DESCRIPTION:
Seale Creek 36.0
END DESCRIPTION:
XS GIS Cut Line= 3
      1350304.98      6817538.01      1350685.08      6817316.98
      1351004.98      6817088.01
#Sta/Elev= 30
  4560.3    2444  4589.7 2440.49  4632.7 2438.34    4670  2434.8  4707.2 2433.48
  4750.3 2434.14  4780.1 2432.46  4803.2 2428.69    4809 2426.62  4824.7 2425.91
  4830.5 2423.73  4846.3    2425    4852 2422.84  4861.1 2423.82  4991.1 2422.24
  5012.6 2421.39  5018.6 2418.93    5019 2418.43  5023.7 2418.93  5042.1 2423.98
  5049.1 2424.48  5142.8  2424.8  5249.7 2432.05  5285.3  2437.4  5300.1 2440.83
  5314.8 2445.92  5335.7 2449.39  5350.4 2454.21  5357.2 2454.88  5393.4 2463.05
#Mann= 4 ,-1 , 0
  4560.3     .07       0  5018.6     .07       0  5023.7     .07       0
  5357.2    .035       0
Bank Sta=5018.6,5023.7
XS Rating Curve= 0 ,0
Exp/Cntr=0.3,0.1

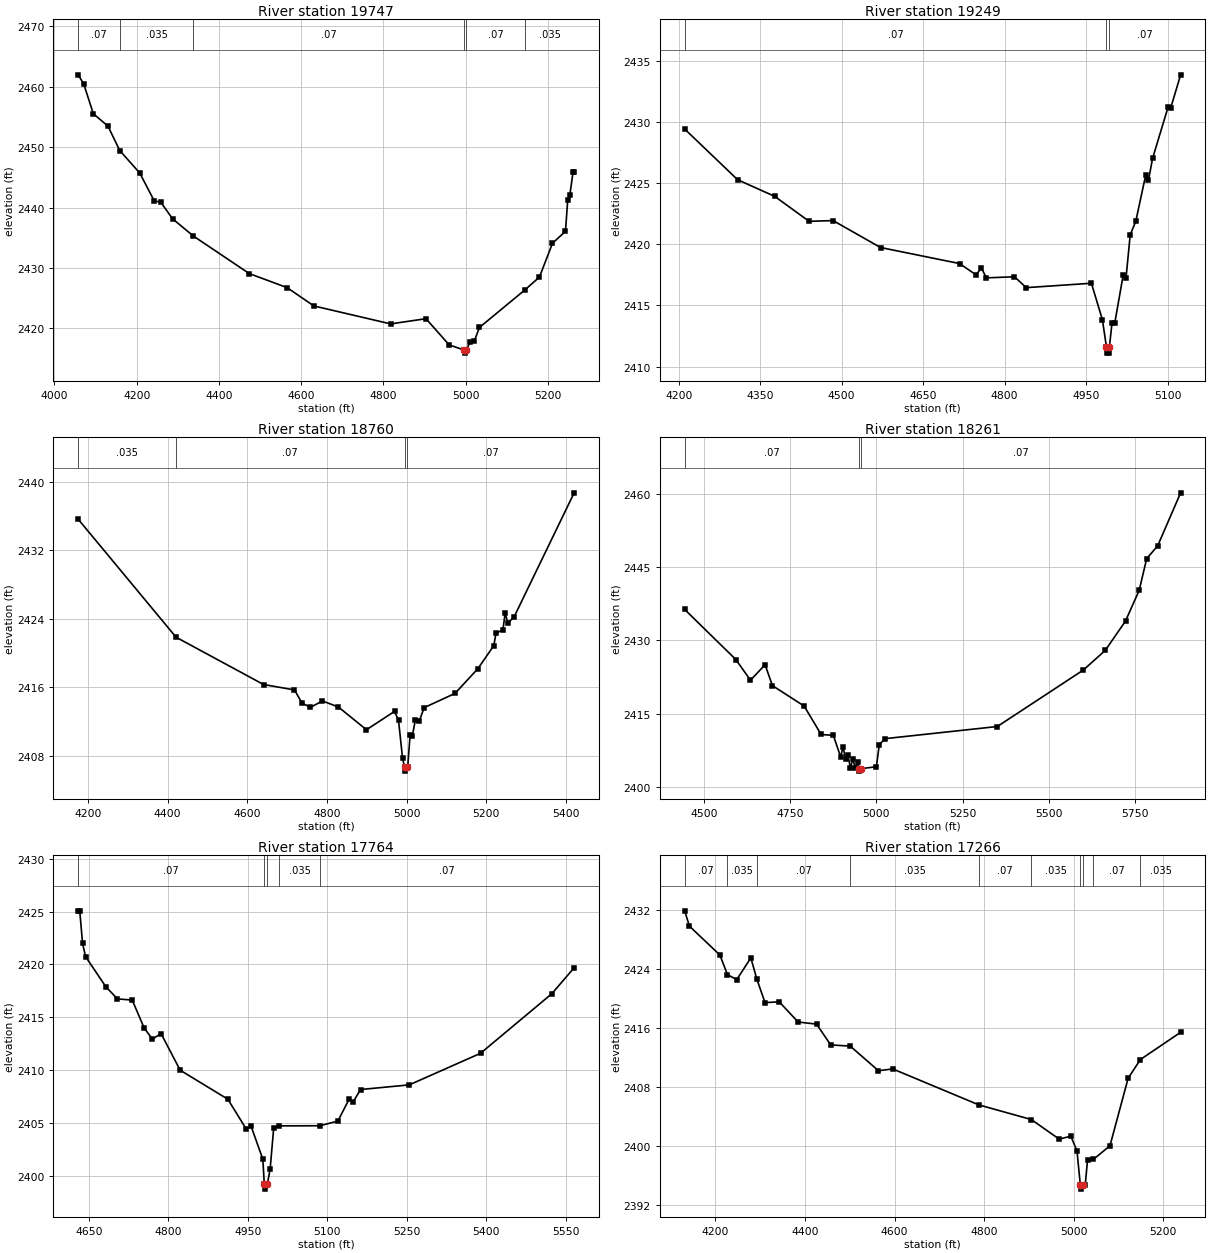
Type RM Length L Ch R = 1 ,19747   ,498,498,498
BEGIN DESCRIPTION:
Seale Creek 35.0
END DESCRIPTION:
XS GIS Cut Line= 3
      1350204.99      6818088.01      1350970.27      6817538.38
      1351054.99      6817288.03
#Sta/Elev= 30
  4057.8 2461.97  4071.3 2460.44  4094.6 2455.53  4130.2 2453.47  4158.9 2449.43
  4207.6  2445.7  4243.2 2441.04    4258 2440.94  4287.4 2438.13  4337.9 2435.28
    4474 2429.06  4566.1 2426.73  4631.2  2423.7  4817.8 2420.73  4903.8 2421.59
  4960.3 2417.25  4997.3 2416.39  4997.7 2415.89  5002.4 2416.39    5011 2417.78
  5021.5 2417.91  5033.9 2420.14  5144.7 2426.37  5179.9 2428.49  5211.5 2434.07
  5243.2 2436.07  5248.6 2441.18  5253.9 2442.13  5261.7 2445.91  5264.3 2445.91
#Mann= 6 ,-1 , 0
  4057.8     .07       0  4158.9    .035       0  4337.9     .07       0
  4997.3     .07       0  5002.4     .07       0  5144.7    .035       0
Bank Sta=4997.3,5002.4
XS Rating Curve= 0 ,0
Exp/Cntr=0.3,0.1

Type RM Length L Ch R = 1 ,19249   ,489,489,489
BEGIN DESCRIPTION:
Seale Creek 34.0
END DESCRIPTION:
XS GIS Cut Line= 3
        1350555.        6817938.      1351334.83      6817818.07
      1351455.03      6817787.99
#Sta/Elev= 30
    4211 2429.41  4308.4 2425.27  4376.7 2423.91    4440 2421.87  4484.2 2421.93
  4571.5 2419.73  4716.9 2418.42  4747.2  2417.5  4757.3 2418.05  4766.3 2417.25
  4818.1 2417.34  4839.7 2416.45  4959.7 2416.81  4979.9 2413.83  4987.4  2411.6
  4987.8  2411.1  4992.3  2411.1  4992.8  2411.6  4997.6 2413.56  5002.7 2413.56
  5018.3 2417.51  5023.4 2417.24  5031.1 2420.77  5041.4 2421.88  5059.5 2425.62
  5064.6 2425.21  5072.3 2427.01  5100.7 2431.19  5105.8 2431.15  5123.9 2433.84
#Mann= 3 ,-1 , 0
    4211     .07       0  4987.4     .07       0  4992.8     .07       0
Bank Sta=4987.4,4992.8
XS Rating Curve= 0 ,0
Exp/Cntr=0.3,0.1

Type RM Length L Ch R = 1 ,18760   ,499,499,499
BEGIN DESCRIPTION:
Seale Creek 33.0
END DESCRIPTION:
XS GIS Cut Line= 3
      1350454.98        6818138.      1351275.28      6818218.12
      1351655.02      6818037.99
#Sta/Elev= 30
  4175.8 2435.64  4421.4 2421.84  4640.9 2416.31  4718.4 2415.68  4737.5 2414.13
  4758.6 2413.64  4788.7 2414.39  4828.9 2413.67  4899.2 2411.02  4969.6 2413.17
  4979.6 2412.11  4989.7 2407.68  4994.6 2406.68    4995 2406.18  5000.1 2406.68
  5002.6 2406.68  5008.6 2410.38  5014.1 2410.25  5021.8 2412.17  5031.3    2412
    5044 2413.61  5121.4 2415.27  5178.8 2418.17  5218.7 2420.86  5224.3 2422.35
  5241.5 2422.67    5247 2424.62  5254.3  2423.5  5269.7 2424.23  5420.3 2438.73
#Mann= 4 ,-1 , 0
  4175.8    .035       0  4421.4     .07       0  4994.6     .07       0
  5000.1     .07       0
Bank Sta=4994.6,5000.1
XS Rating Curve= 0 ,0
Exp/Cntr=0.3,0.1

Type RM Length L Ch R = 1 ,18261   ,497,497,497
BEGIN DESCRIPTION:
Seale Creek 32.0
END DESCRIPTION:
XS GIS Cut Line= 3
      1350655.03      6818887.97      1351047.27      6818493.64
      1351855.04      6818137.98
#Sta/Elev= 30
  4443.8 2436.33  4592.3 2426.08  4634.7 2421.85  4677.1 2425.03  4698.3 2420.75
  4790.3 2416.57  4839.7 2410.75  4875.1 2410.56  4896.3 2406.16  4903.4 2408.27
  4910.4  2405.7  4917.5 2406.55  4924.6 2403.92  4931.7 2405.75  4938.7 2403.89
  4945.8 2405.16    4950 2403.75  4950.4 2403.25  4955.8 2403.75    5000 2404.16
  5008.4 2408.68  5025.6  2409.9  5350.8 2412.38  5600.6 2423.95    5664 2427.96
  5722.7 2433.96  5762.4 2440.26  5784.2 2446.74    5816 2449.35  5882.6  2460.2
#Mann= 3 ,-1 , 0
  4443.8     .07       0    4950     .07       0  4955.8     .07       0
Bank Sta=4950,4955.8
XS Rating Curve= 0 ,0
Exp/Cntr=0.3,0.1

Type RM Length L Ch R = 1 ,17764   ,498,498,498
BEGIN DESCRIPTION:
Seale Creek 31.0
END DESCRIPTION:
XS GIS Cut Line= 3
      1350954.97      6818988.02       1351281.8      6818814.36
      1351704.97      6818438.03
#Sta/Elev= 30
  4629.9 2425.07  4632.8 2425.07  4638.1 2421.99  4643.8 2420.73  4682.1 2417.88
    4704 2416.73  4731.9 2416.62  4754.5 2413.97    4770 2412.92  4786.3 2413.45
  4822.4 2409.98  4912.5 2407.23    4947 2404.42  4956.5 2404.65  4978.5 2401.55
  4981.2 2399.22  4981.7 2398.72  4987.1 2399.22  4992.3 2400.63    4999  2404.5
  5009.2 2404.71    5086 2404.72  5120.2 2405.16  5141.1 2407.21  5148.7 2406.94
  5162.9 2408.15  5254.9 2408.59  5389.5 2411.58  5524.1 2417.22  5566.3 2419.68
#Mann= 5 ,-1 , 0
  4629.9     .07       0  4981.2     .07       0  4987.1     .07       0
  5009.2    .035       0    5086     .07       0
Bank Sta=4981.2,4987.1
XS Rating Curve= 0 ,0
Exp/Cntr=0.3,0.1

Type RM Length L Ch R = 1 ,17266   ,497,497,497
BEGIN DESCRIPTION:
Seale Creek 30.0
END DESCRIPTION:
XS GIS Cut Line= 3
      1350854.97      6819238.01      1351678.13      6818961.69
      1351904.97      6818888.01
#Sta/Elev= 30
  4131.7  2431.9  4142.2 2429.83  4210.3 2425.91  4227.1 2423.27  4247.8 2422.57
  4279.4 2425.53  4292.7 2422.65    4311 2419.46  4342.7 2419.57  4384.9 2416.83
    4426 2416.55  4457.6 2413.73  4501.2 2413.57  4564.2 2410.23  4595.9 2410.48
  4788.4  2405.6  4905.3 2403.62  4967.4 2400.97  4993.6 2401.36  5007.2 2399.37
  5014.8 2394.69  5015.3 2394.19  5020.7 2394.69  5025.6 2394.77  5030.8 2398.14
  5043.6 2398.21  5080.8 2400.06  5121.4 2409.22  5148.7 2411.75  5238.5 2415.44
#Mann= 10 ,-1 , 0
  4131.7     .07       0  4227.1    .035       0  4292.7     .07       0
  4501.2    .035       0  4788.4     .07       0  4905.3    .035       0
  5014.8    .035       0  5020.7    .035       0  5043.6     .07       0
  5148.7    .035       0
Bank Sta=5014.8,5020.7
XS Rating Curve= 0 ,0
Exp/Cntr=0.3,0.1

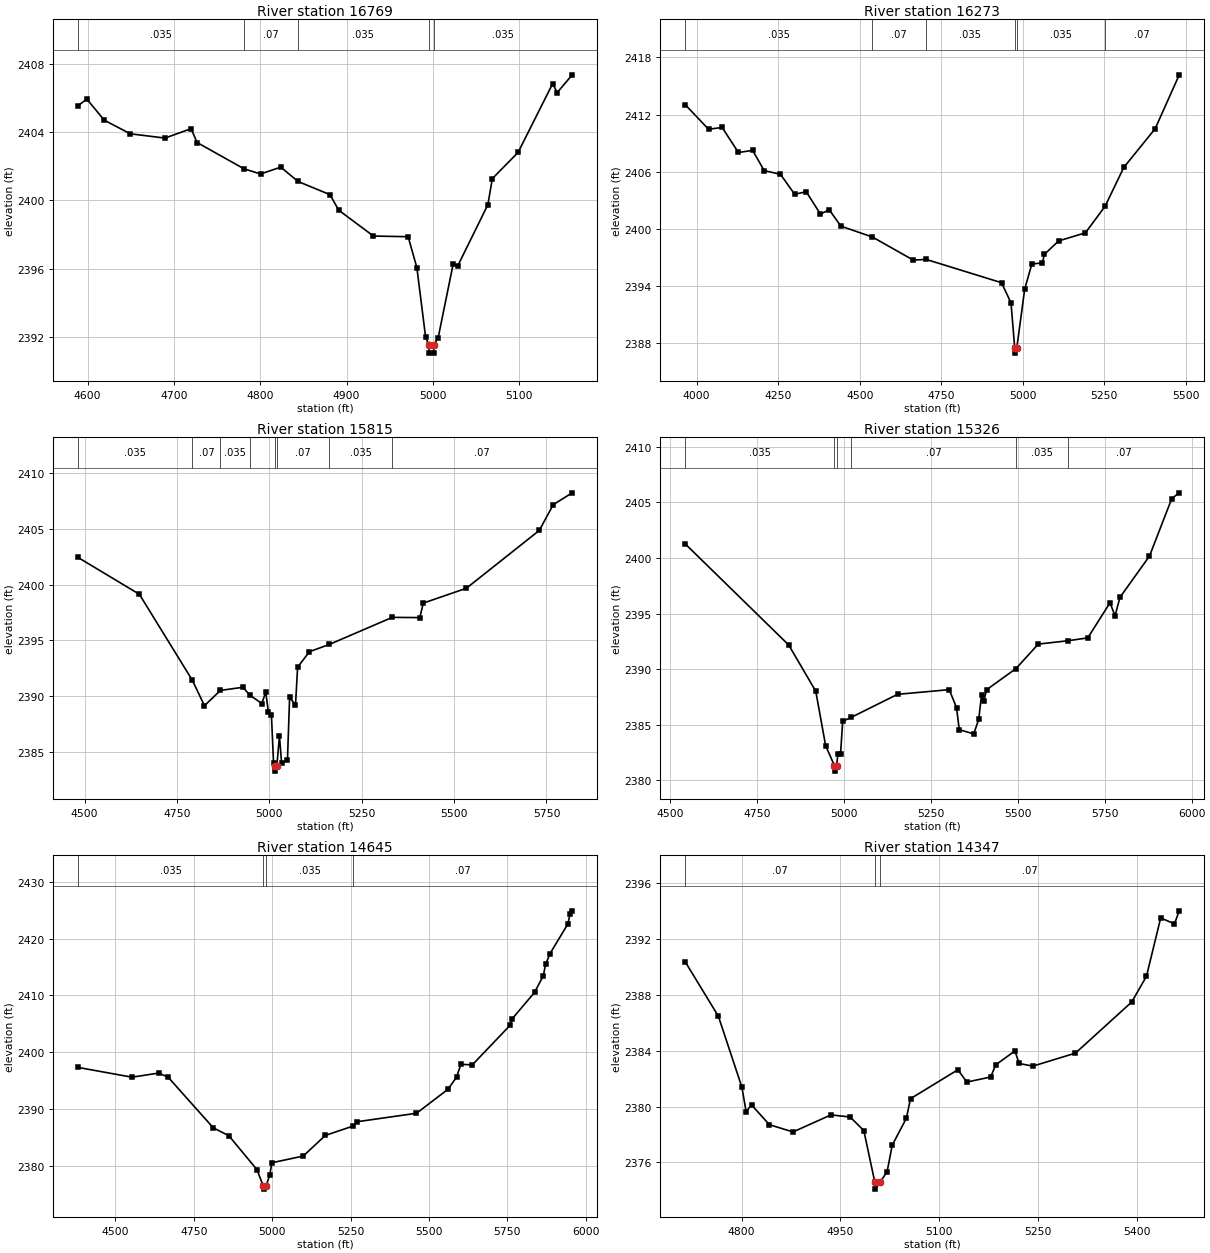
Type RM Length L Ch R = 1 ,16769   ,496,496,496
BEGIN DESCRIPTION:
Seale Creek 29.0
END DESCRIPTION:
XS GIS Cut Line= 3
      1351554.96        6819338.      1351963.49      6819293.91
      1352004.99      6819138.04
#Sta/Elev= 30
  4589.1 2405.54  4599.2 2405.92  4619.3 2404.69  4649.5 2403.89  4689.7 2403.64
  4719.9 2404.19  4726.9 2403.38  4781.3 2401.84  4800.4 2401.54  4823.8 2401.94
  4843.8  2401.1  4880.8 2400.33  4890.9 2399.42  4931.1 2397.91  4971.3 2397.87
  4981.4 2396.06  4991.5    2392  4995.2 2391.56  4995.7 2391.06  5000.7 2391.06
  5001.2 2391.56  5006.1 2391.97  5023.5 2396.29  5028.6 2396.15  5063.6 2399.74
  5068.8 2401.27  5098.6  2402.8  5138.7 2406.83  5143.9  2406.3  5161.3 2407.34
#Mann= 5 ,-1 , 0
  4589.1    .035       0  4781.3     .07       0  4843.8    .035       0
  4995.2    .035       0  5001.2    .035       0
Bank Sta=4995.2,5001.2
XS Rating Curve= 0 ,0
Exp/Cntr=0.3,0.1

Type RM Length L Ch R = 1 ,16273   ,458,458,458
BEGIN DESCRIPTION:
Seale Creek 28.0
END DESCRIPTION:
XS GIS Cut Line= 3
      1351405.03      6820287.98      1352228.73      6819661.12
      1352454.99      6819238.02
#Sta/Elev= 30
  3964.9 2413.04  4036.6 2410.45  4078.2 2410.64  4128.2 2408.01  4171.7 2408.23
  4207.1 2406.11    4257 2405.72  4300.6 2403.62    4336 2403.89  4379.6 2401.54
  4406.7 2401.99  4442.4 2400.27    4539 2399.13  4664.5  2396.7  4703.4 2396.78
  4934.8 2394.33  4963.9 2392.21  4975.4 2387.43  4975.9 2386.93  4981.5 2387.43
    5006 2393.68  5027.9  2396.3  5060.2  2396.4  5066.1  2397.3    5110 2398.72
  5192.1 2399.57  5252.4 2402.36  5309.7 2406.44  5405.9 2410.51  5479.8 2416.17
#Mann= 6 ,-1 , 0
  3964.9    .035       0    4539     .07       0  4703.4    .035       0
  4975.4    .035       0  4981.5    .035       0  5252.4     .07       0
Bank Sta=4975.4,4981.5
XS Rating Curve= 0 ,0
Exp/Cntr=0.3,0.1

Type RM Length L Ch R = 1 ,15815   ,489,489,489
BEGIN DESCRIPTION:
Seale Creek 27.0
END DESCRIPTION:
XS GIS Cut Line= 3
      1351904.95      6820188.01      1352404.58      6820053.18
      1352804.98      6819338.04
#Sta/Elev= 30
  4482.5 2402.44  4648.3 2399.14  4791.6 2391.43  4824.4 2389.15  4867.7 2390.52
  4928.5  2390.8  4946.7 2390.11  4979.7 2389.34  4990.1 2390.37  4997.6 2388.54
  5005.6 2388.32  5011.4 2383.99  5014.3 2383.78  5014.8 2383.28  5020.4 2383.78
  5027.3 2386.43  5033.1 2384.02    5049 2384.25  5054.8 2389.89  5070.7  2389.2
  5076.5  2392.6  5108.4 2393.99  5162.1 2394.64  5332.6 2397.07  5407.1 2397.05
  5416.6 2398.35  5533.1 2399.68  5730.6 2404.87  5768.3 2407.18  5819.6 2408.24
#Mann= 8 ,-1 , 0
  4482.5    .035       0  4791.6     .07       0  4867.7    .035       0
  4946.7     .07       0  5014.3     .07       0  5020.4     .07       0
  5162.1    .035       0  5332.6     .07       0
Bank Sta=5014.3,5020.4
XS Rating Curve= 0 ,0
Exp/Cntr=0.3,0.1

Type RM Length L Ch R = 1 ,15326   ,681,681,681
BEGIN DESCRIPTION:
Seale Creek 26.0
END DESCRIPTION:
XS GIS Cut Line= 3
      1352055.02      6820837.98      1352354.36      6820493.58
      1353105.03      6819887.98
#Sta/Elev= 30
  4543.7 2401.28  4841.4 2392.18  4919.2 2388.02  4947.7 2383.11  4972.9 2381.33
  4973.4 2380.83  4979.4 2381.33  4982.8 2382.38  4990.4 2382.33  4996.7 2385.32
  5021.4 2385.67  5154.4 2387.74  5303.1 2388.16    5324 2386.54  5331.9 2384.56
  5373.5 2384.18  5387.9 2385.49  5395.9 2387.69  5402.3  2387.1  5410.3 2388.15
  5495.1 2390.06    5559 2392.26  5644.3 2392.56  5701.4 2392.82  5765.4 2395.98
  5779.7  2394.8  5794.1 2396.47  5878.9 2400.18  5942.9 2405.35  5964.5 2405.87
#Mann= 6 ,-1 , 0
  4543.7    .035       0  4972.9    .035       0  4979.4    .035       0
  5021.4     .07       0  5495.1    .035       0  5644.3     .07       0
Bank Sta=4972.9,4979.4
XS Rating Curve= 0 ,0
Exp/Cntr=0.3,0.1

Type RM Length L Ch R = 1 ,14645   ,298,298,298
BEGIN DESCRIPTION:
Seale Creek 25.0
END DESCRIPTION:
XS GIS Cut Line= 3
      1352355.03      6820887.99      1352931.84      6820664.21
      1353554.98      6819938.02
#Sta/Elev= 30
  4381.3 2397.34  4552.9 2395.62  4638.6 2396.35  4668.5 2395.61  4812.7 2386.69
  4861.8 2385.33  4951.6 2379.35    4972 2376.42  4972.5 2375.92  4980.2 2376.42
  4992.7 2378.44    4999 2380.56  5099.2 2381.74  5169.5 2385.37  5258.7 2387.03
  5269.4 2387.77  5460.3 2389.27  5560.2 2393.47    5588 2395.61  5601.9  2397.9
  5638.1 2397.78  5758.8 2404.75  5765.4 2405.89  5836.8 2410.55  5864.7 2413.47
  5871.9 2415.46  5886.1 2417.38  5943.2  2422.6  5949.8 2424.33  5956.9  2424.9
#Mann= 4 ,-1 , 0
  4381.3    .035       0    4972    .035       0  4980.2    .035       0
  5258.7     .07       0
Bank Sta=4972,4980.2
XS Rating Curve= 0 ,0
Exp/Cntr=0.3,0.1

Type RM Length L Ch R = 1 ,14347   ,494,494,494
BEGIN DESCRIPTION:
Seale Creek 24.0
END DESCRIPTION:
XS GIS Cut Line= 3
      1353004.97      6821038.04      1353178.58      6820811.01
      1353455.02      6820437.97
#Sta/Elev= 30
  4714.2 2390.36  4764.6 2386.46  4800.4 2381.37  4806.7 2379.64    4815 2380.11
  4842.1  2378.7  4877.9 2378.18  4935.5  2379.4  4964.6 2379.25  4985.4 2378.28
  5002.1 2374.59  5002.6 2374.09  5010.3 2374.59  5020.8 2375.35  5028.6 2377.24
    5050 2379.16  5056.3 2380.56  5128.2 2382.63  5141.8 2381.75    5178 2382.11
  5185.7 2382.98  5214.9 2383.98  5221.1 2383.08    5242 2382.89  5306.7 2383.82
  5392.2 2387.48  5414.5 2389.32  5436.1 2393.49    5457 2393.07  5464.3    2394
#Mann= 3 ,-1 , 0
  4714.2     .07       0  5002.1     .07       0  5010.3     .07       0
Bank Sta=5002.1,5010.3
XS Rating Curve= 0 ,0
Exp/Cntr=0.3,0.1

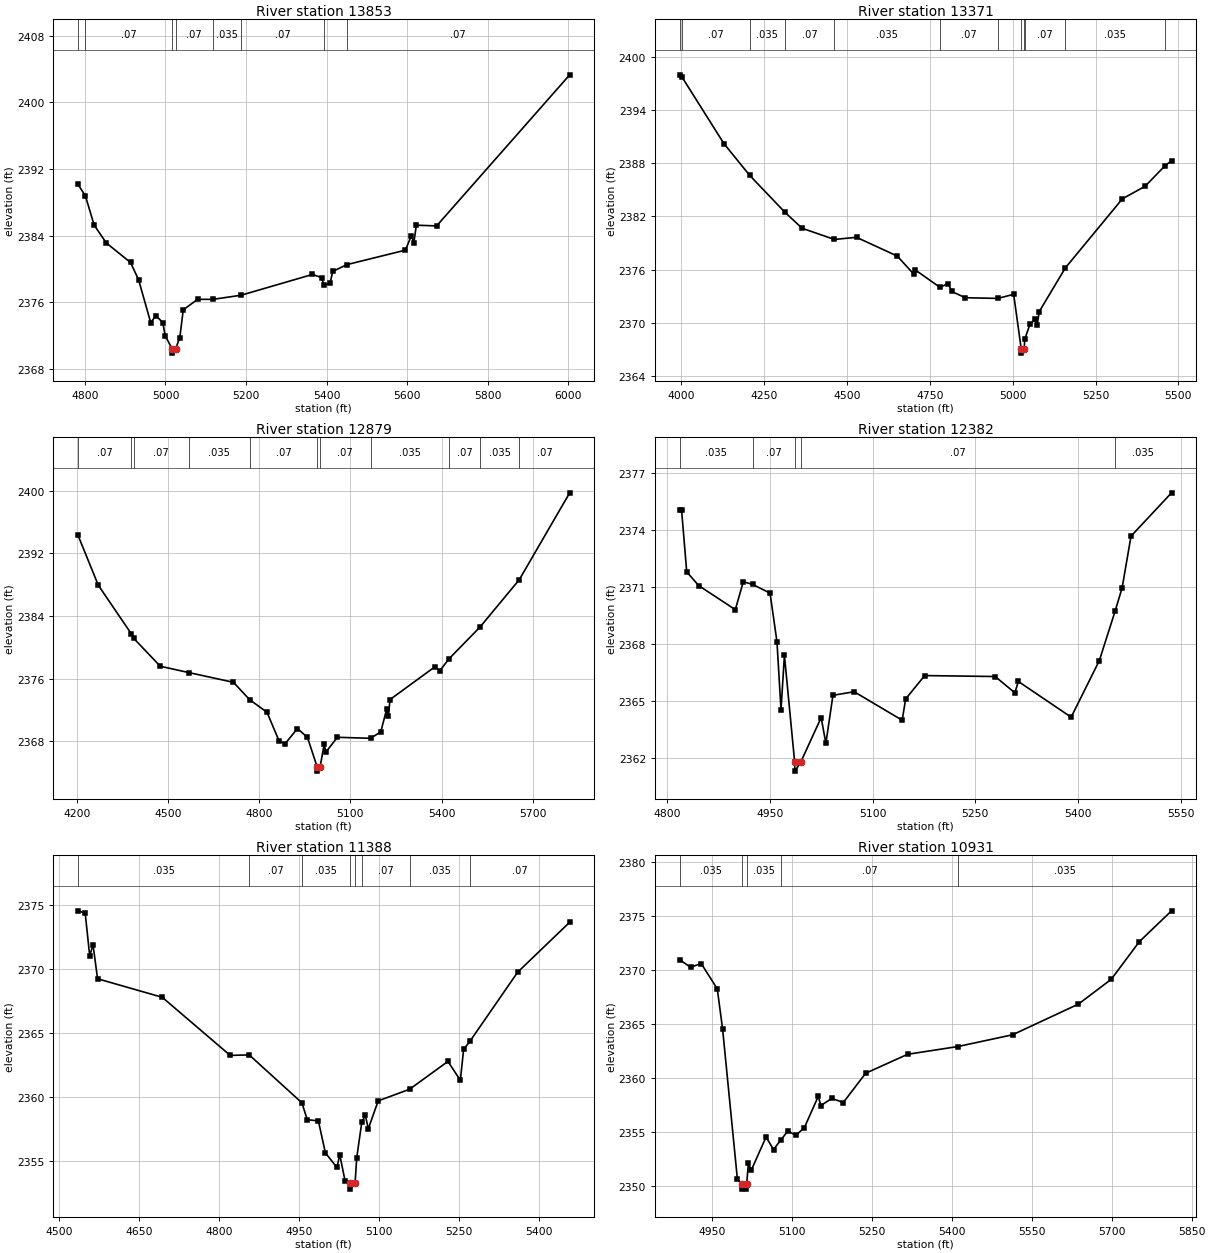
Type RM Length L Ch R = 1 ,13853   ,482,482,482
BEGIN DESCRIPTION:
Seale Creek 23.0
END DESCRIPTION:
XS GIS Cut Line= 3
      1353104.98        6821138.      1353321.51      6821155.04
        1353905.        6820338.
#Sta/Elev= 30
  4782.8 2390.16  4801.2 2388.77  4822.9 2385.27    4853 2383.13  4913.2 2380.78
  4933.3  2378.7  4963.4 2373.55  4976.2  2374.4  4993.5 2373.55  4999.2 2371.99
  5016.8 2370.39  5017.3 2369.89    5025 2370.39  5035.6 2371.75  5044.2 2375.09
  5079.8 2376.35    5118 2376.35  5187.4 2376.84    5365 2379.34  5388.3 2378.96
  5393.4 2378.02  5409.2 2378.32  5415.3  2379.7  5450.5 2380.52    5596 2382.26
  5610.7    2384  5616.9 2383.15  5623.1 2385.26  5673.4 2385.17    6004 2403.32
#Mann= 8 ,-1 , 0
  4782.8    .035       0  4801.2     .07       0  5016.8     .07       0
    5025     .07       0    5118    .035       0  5187.4     .07       0
  5393.4    .035       0  5450.5     .07       0
Bank Sta=5016.8,5025
XS Rating Curve= 0 ,0
Exp/Cntr=0.3,0.1

Type RM Length L Ch R = 1 ,13371   ,492,492,492
BEGIN DESCRIPTION:
Seale Creek 22.0
END DESCRIPTION:
XS GIS Cut Line= 3
      1352704.97      6821638.01       1353684.7      6821418.12
      1354105.02      6821187.99
#Sta/Elev= 30
  3995.9 2397.99  4003.1  2397.7  4129.2 2390.21  4206.8 2386.63  4313.2 2382.46
  4364.9 2380.66  4462.2  2379.4  4528.9 2379.64  4651.9 2377.52  4700.9 2375.51
    4706 2375.96  4780.6 2373.99  4805.6 2374.42  4815.8 2373.53  4856.8 2372.82
  4955.4 2372.74    5003  2373.2  5025.7 2367.06  5026.2 2366.56  5034.7 2367.06
  5036.4 2368.12    5052 2369.81  5068.1 2370.38  5073.8  2369.7  5080.1 2371.25
  5158.8 2376.18    5331 2383.99  5399.4  2385.4    5459  2387.7  5479.2 2388.29
#Mann= 12 ,-1 , 0
  3995.9    .035       0  4003.1     .07       0  4206.8    .035       0
  4313.2     .07       0  4462.2    .035       0  4780.6     .07       0
  4955.4    .035       0  5025.7    .035       0  5034.7    .035       0
  5036.4     .07       0  5158.8    .035       0    5459     .07       0
Bank Sta=5025.7,5034.7
XS Rating Curve= 0 ,0
Exp/Cntr=0.3,0.1

Type RM Length L Ch R = 1 ,12879   ,497,497,497
BEGIN DESCRIPTION:
Seale Creek 21.0
END DESCRIPTION:
XS GIS Cut Line= 3
      1352804.98        6821738.      1353598.95      6821796.16
      1354404.98        6821638.
#Sta/Elev= 30
  4203.9 2394.29  4270.7 2387.91  4379.5  2381.7  4386.7 2381.15  4474.6 2377.57
  4567.4 2376.77  4715.3 2375.52  4768.5  2373.3  4825.6  2371.7  4865.7    2368
  4885.7  2367.7  4925.8 2369.62  4958.8 2368.48  4990.9 2364.68  4991.4 2364.18
  5000.1 2364.68  5013.8 2367.62  5018.9 2366.59  5057.1  2368.5  5166.3 2368.37
  5199.8 2369.19  5219.6 2372.13  5224.7  2371.2  5230.4 2373.32    5379 2377.53
  5393.4 2376.96  5424.6 2378.53    5526 2382.56  5655.5 2388.62  5821.4 2399.71
#Mann= 11 ,-1 , 0
  4203.9     .07       0  4379.5    .035       0  4386.7     .07       0
  4567.4    .035       0  4768.5     .07       0  4990.9     .07       0
  5000.1     .07       0  5166.3    .035       0  5424.6     .07       0
    5526    .035       0  5655.5     .07       0
Bank Sta=4990.9,5000.1
XS Rating Curve= 0 ,0
Exp/Cntr=0.3,0.1

Type RM Length L Ch R = 1 ,12382   ,994,994,994
BEGIN DESCRIPTION:
Seale Creek 20.0
END DESCRIPTION:
XS GIS Cut Line= 3
      1353205.02        6822138.      1353384.33      6822168.59
        1353905.        6822038.
#Sta/Elev= 30
  4818.1  2375.1  4820.6  2375.1  4828.2 2371.82  4845.6  2371.1  4899.2 2369.83
  4910.9  2371.3  4924.4 2371.16    4950  2370.7  4960.1 2368.14    4966 2364.56
    4971 2367.42  4985.9 2361.83  4986.4 2361.33  4995.2 2361.83  5024.7 2364.15
  5031.6 2362.79  5041.9 2365.32  5072.9 2365.51  5143.1 2364.01  5148.2 2365.13
    5176 2366.36  5279.1 2366.31  5307.8 2365.45  5312.9 2366.05  5390.1 2364.17
  5431.3 2367.15  5454.5 2369.77  5464.6 2370.98  5477.6  2373.7  5536.8 2375.98
#Mann= 5 ,-1 , 0
  4818.1    .035       0  4924.4     .07       0  4985.9     .07       0
  4995.2     .07       0  5454.5    .035       0
Bank Sta=4985.9,4995.2
XS Rating Curve= 0 ,0
Exp/Cntr=0.3,0.1

Type RM Length L Ch R = 1 ,11388   ,457,457,457
BEGIN DESCRIPTION:
Seale Creek 19.0
END DESCRIPTION:
XS GIS Cut Line= 3
      1353354.99      6822287.99      1353731.18      6822561.14
      1354154.98      6822388.01
#Sta/Elev= 30
  4535.1 2374.58  4548.6  2374.4  4557.1 2371.04  4563.3 2371.93  4571.8 2369.26
  4693.2 2367.81  4820.7 2363.26  4856.4  2363.3  4955.2 2359.55  4965.3 2358.23
  4986.2 2358.13  4999.3 2355.63  5020.9 2354.49  5026.3 2355.47  5036.5 2353.39
  5045.6 2353.29  5046.1 2352.79  5055.1 2353.29  5058.1 2355.24  5067.8 2358.07
  5074.4 2358.56  5079.8 2357.51  5098.4  2359.7  5157.3 2360.61  5229.3 2362.79
  5252.6 2361.31  5258.7 2363.73  5270.8 2364.38  5360.2 2369.78  5457.8 2373.69
#Mann= 8 ,-1 , 0
  4535.1    .035       0  4856.4     .07       0  4955.2    .035       0
  5045.6    .035       0  5055.1    .035       0  5067.8     .07       0
  5157.3    .035       0  5270.8     .07       0
Bank Sta=5045.6,5055.1
XS Rating Curve= 0 ,0
Exp/Cntr=0.3,0.1

Type RM Length L Ch R = 1 ,10931   ,1000,1000,1000
BEGIN DESCRIPTION:
Seale Creek 18.0
END DESCRIPTION:
XS GIS Cut Line= 3
        1353355.        6822888.      1353465.34      6822877.88
      1354255.03      6822687.99
#Sta/Elev= 30
  4889.2 2370.95  4909.3 2370.26  4929.4  2370.6  4959.5 2368.26  4969.5 2364.54
  4997.3  2350.6  5005.2 2350.19  5005.7 2349.69  5014.2 2349.69  5014.7 2350.19
    5018  2352.1  5023.1 2351.42  5051.1 2354.52  5065.1 2353.36  5078.8 2354.25
  5092.2 2355.08    5107 2354.67  5123.1  2355.4    5149 2358.28  5154.1 2357.44
  5174.5  2358.1  5196.1 2357.72    5238 2360.43  5316.8 2362.19  5411.2 2362.91
  5513.9    2364  5637.3 2366.84    5699 2369.14  5751.8 2372.63  5812.2 2375.49
#Mann= 5 ,-1 , 0
  4889.2    .035       0  5005.2    .035       0  5014.7    .035       0
  5078.8     .07       0  5411.2    .035       0
Bank Sta=5005.2,5014.7
XS Rating Curve= 0 ,0
Exp/Cntr=0.3,0.1

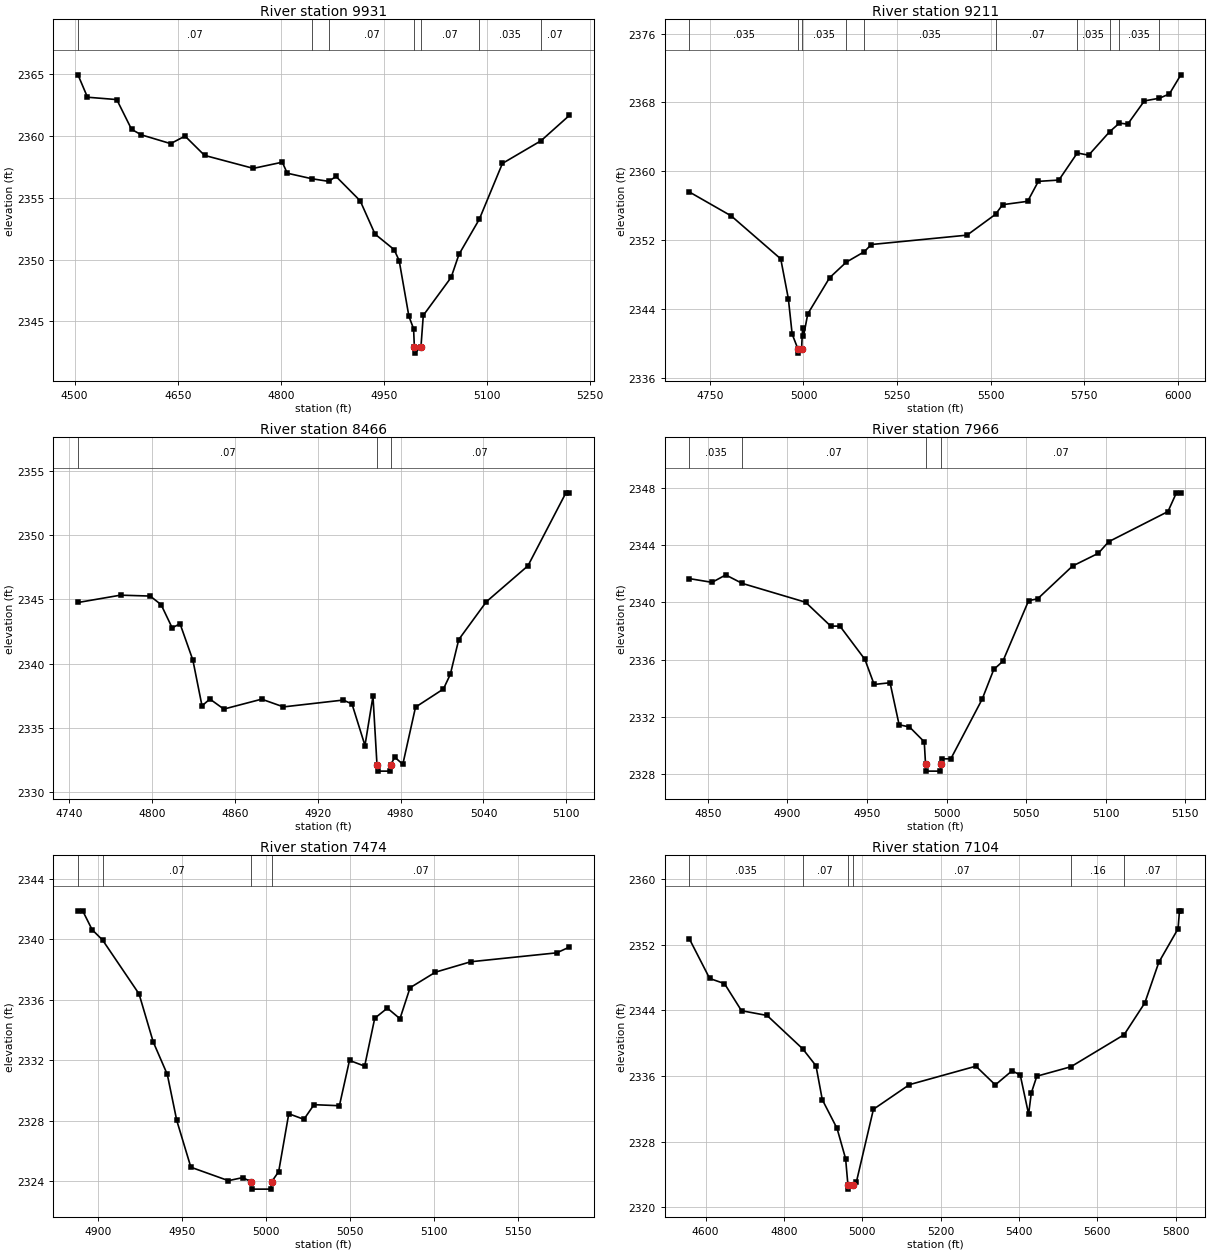
Type RM Length L Ch R = 1 ,9931    ,720,720,720
BEGIN DESCRIPTION:
Seale Creek 17.0
END DESCRIPTION:
XS GIS Cut Line= 3
      1353355.03      6823138.03      1353687.98      6823504.59
      1353905.03        6823538.
#Sta/Elev= 30
  4504.8 2364.93  4518.6 2363.12  4561.2 2362.93  4582.8 2360.52    4597 2360.08
  4639.6 2359.37  4660.5 2359.98  4688.9 2358.42  4759.9 2357.37    4802 2357.87
  4809.2 2356.98  4845.2 2356.53  4869.6 2356.32  4880.1 2356.72  4915.3 2354.75
  4936.9 2352.06  4964.6 2350.81    4972 2349.92  4986.2 2345.41    4993 2344.41
  4994.1 2342.94  4994.6 2342.44  5003.7 2342.94  5007.1 2345.49  5047.6 2348.56
    5059 2350.42  5088.6 2353.26  5122.2 2357.77  5178.3  2359.6  5219.6 2361.65
#Mann= 7 ,-1 , 0
  4504.8     .07       0  4845.2    .035       0  4869.6     .07       0
  4994.1     .07       0  5003.7     .07       0  5088.6    .035       0
  5178.3     .07       0
Bank Sta=4994.1,5003.7
XS Rating Curve= 0 ,0
Exp/Cntr=0.3,0.1

Type RM Length L Ch R = 1 ,9211    ,745,745,745
BEGIN DESCRIPTION:
Seale Creek 16.0
END DESCRIPTION:
XS GIS Cut Line= 3
      1353005.04      6823988.01      1353304.84      6824043.02
      1354204.97      6823588.01
#Sta/Elev= 30
  4695.2 2357.58    4807  2354.8  4939.2 2349.81  4959.5  2345.2  4969.7 2341.07
    4985 2339.36  4985.5 2338.86  4994.9 2339.36  4997.5 2341.79    5000 2340.81
  5011.4 2343.42  5069.8 2347.62  5114.3 2349.43  5162.4 2350.64  5181.2 2351.48
  5437.2 2352.57  5513.2 2354.99  5532.2 2356.11  5599.1  2356.5  5627.7 2358.82
  5682.6 2358.97  5731.8 2362.12  5762.1 2361.86  5818.1 2364.58  5844.3 2365.59
  5866.6 2365.47  5911.1 2368.17  5951.2 2368.48    5978 2368.98  6008.6  2371.2
#Mann= 10 ,-1 , 0
  4695.2    .035       0    4985    .035       0  4994.9    .035       0
  5114.3     .07       0  5162.4    .035       0  5513.2     .07       0
  5731.8    .035       0  5818.1     .07       0  5844.3    .035       0
  5951.2     .07       0
Bank Sta=4985,4994.9
XS Rating Curve= 0 ,0
Exp/Cntr=0.3,0.1

Type RM Length L Ch R = 1 ,8466    ,500,500,500
BEGIN DESCRIPTION:
Seale Creek 15.0
END DESCRIPTION:
XS GIS Cut Line= 3
      1353482.75      6824657.94      1353702.94      6824532.14
      1353804.98        6824538.
#Sta/Elev= 30
  4746.4 2344.76  4777.2 2345.33  4798.7 2345.26  4806.6 2344.59  4814.6 2342.79
  4820.3 2343.11  4829.6 2340.28  4836.2 2336.73  4841.9 2337.26    4852 2336.48
  4879.4 2337.25  4895.2 2336.65  4938.4 2337.18  4944.8 2336.88  4954.2 2333.65
    4960 2337.48  4962.9 2332.16  4963.4 2331.66  4972.3 2331.66  4972.8 2332.16
  4975.8 2332.74  4981.6 2332.19  4990.8 2336.63    5011 2338.04    5016 2339.18
  5022.1 2341.88  5042.1 2344.82  5072.2 2347.61  5099.7 2353.28  5102.2 2353.28
#Mann= 3 ,-1 , 0
  4746.4     .07       0  4962.9     .07       0  4972.8     .07       0
Bank Sta=4962.9,4972.8
XS Rating Curve= 0 ,0
Exp/Cntr=0.3,0.1

Type RM Length L Ch R = 1 ,7966    ,492,492,492
BEGIN DESCRIPTION:
Seale Creek 14.0
END DESCRIPTION:
XS GIS Cut Line= 3
      1353695.31      6824898.74      1353835.13      6824817.71
      1353904.98      6824688.03
#Sta/Elev= 30
  4838.4 2341.66  4852.6  2341.4  4861.2 2341.92  4871.5 2341.33  4911.4 2340.01
  4927.2 2338.34    4933 2338.34  4948.7 2336.01  4954.5 2334.26  4964.5 2334.38
  4970.2 2331.44  4976.7 2331.29    4986 2330.25  4986.8  2328.7  4987.3  2328.2
  4996.2  2328.2  4996.7  2328.7    4997 2329.06  5002.7 2329.06  5022.4 2333.23
  5029.7 2335.31  5035.4 2335.88  5051.6 2340.12  5057.3 2340.25  5079.2 2342.54
  5095.4 2343.43  5101.9 2344.24  5139.2 2346.35  5144.5 2347.66  5147.3 2347.66
#Mann= 4 ,-1 , 0
  4838.4    .035       0  4871.5     .07       0  4986.8     .07       0
  4996.7     .07       0
Bank Sta=4986.8,4996.7
XS Rating Curve= 0 ,0
Exp/Cntr=0.3,0.1

Type RM Length L Ch R = 1 ,7474    ,370,370,370
BEGIN DESCRIPTION:
Seale Creek 13.0
END DESCRIPTION:
XS GIS Cut Line= 3
        1353905.        6825338.        1353955.        6825238.
      1354055.01      6825087.98
#Sta/Elev= 30
  4888.2 2341.89    4891 2341.89  4896.6 2340.64  4902.8 2339.96  4924.5 2336.39
  4932.9 2333.22  4941.3 2331.06  4946.9 2328.02  4955.3 2324.92  4977.6 2324.03
    4986 2324.23    4991 2323.97  4991.5 2323.47  5002.9 2323.47  5003.4 2323.97
  5007.5 2324.63  5013.5 2328.46  5022.5 2328.09  5028.5 2329.06  5043.6 2328.99
  5049.6 2331.99  5058.6 2331.61  5064.6 2334.78  5072.1 2335.45  5079.6 2334.75
  5085.6  2336.8  5100.7 2337.83  5121.7 2338.52  5172.8 2339.11  5180.3 2339.49
#Mann= 4 ,-1 , 0
  4888.2    .035       0  4902.8     .07       0    4991     .07       0
  5003.4     .07       0
Bank Sta=4991,5003.4
XS Rating Curve= 0 ,0
Exp/Cntr=0.3,0.1

Type RM Length L Ch R = 1 ,7104    ,492,492,492
BEGIN DESCRIPTION:
Seale Creek 12.0
END DESCRIPTION:
XS GIS Cut Line= 3
        1354005.      6825837.99       1354218.3      6825451.55
      1354804.99      6824888.01
#Sta/Elev= 30
  4558.6 2352.68  4610.2 2347.88    4648 2347.25  4691.5 2343.95  4756.8 2343.37
  4847.7 2339.31  4881.7 2337.24  4897.8 2333.11  4935.5 2329.61  4957.4 2325.91
  4963.3 2322.71  4963.8 2322.21  4976.2 2322.71  4984.9 2323.08  5028.4 2331.94
  5120.3 2334.94  5290.1 2337.19  5339.7 2334.91  5382.2 2336.62  5403.3 2336.13
  5424.7 2331.34  5431.6 2333.93  5445.7 2335.97  5532.7 2337.12  5668.7 2341.03
  5721.5  2344.9  5757.1 2349.83  5806.4 2353.94    5810 2356.12  5813.5 2356.12
#Mann= 6 ,-1 , 0
  4558.6    .035       0  4847.7     .07       0  4963.3     .07       0
  4976.2     .07       0  5532.7     .16       0  5668.7     .07       0
Bank Sta=4963.3,4976.2
XS Rating Curve= 0 ,0
Exp/Cntr=0.3,0.1