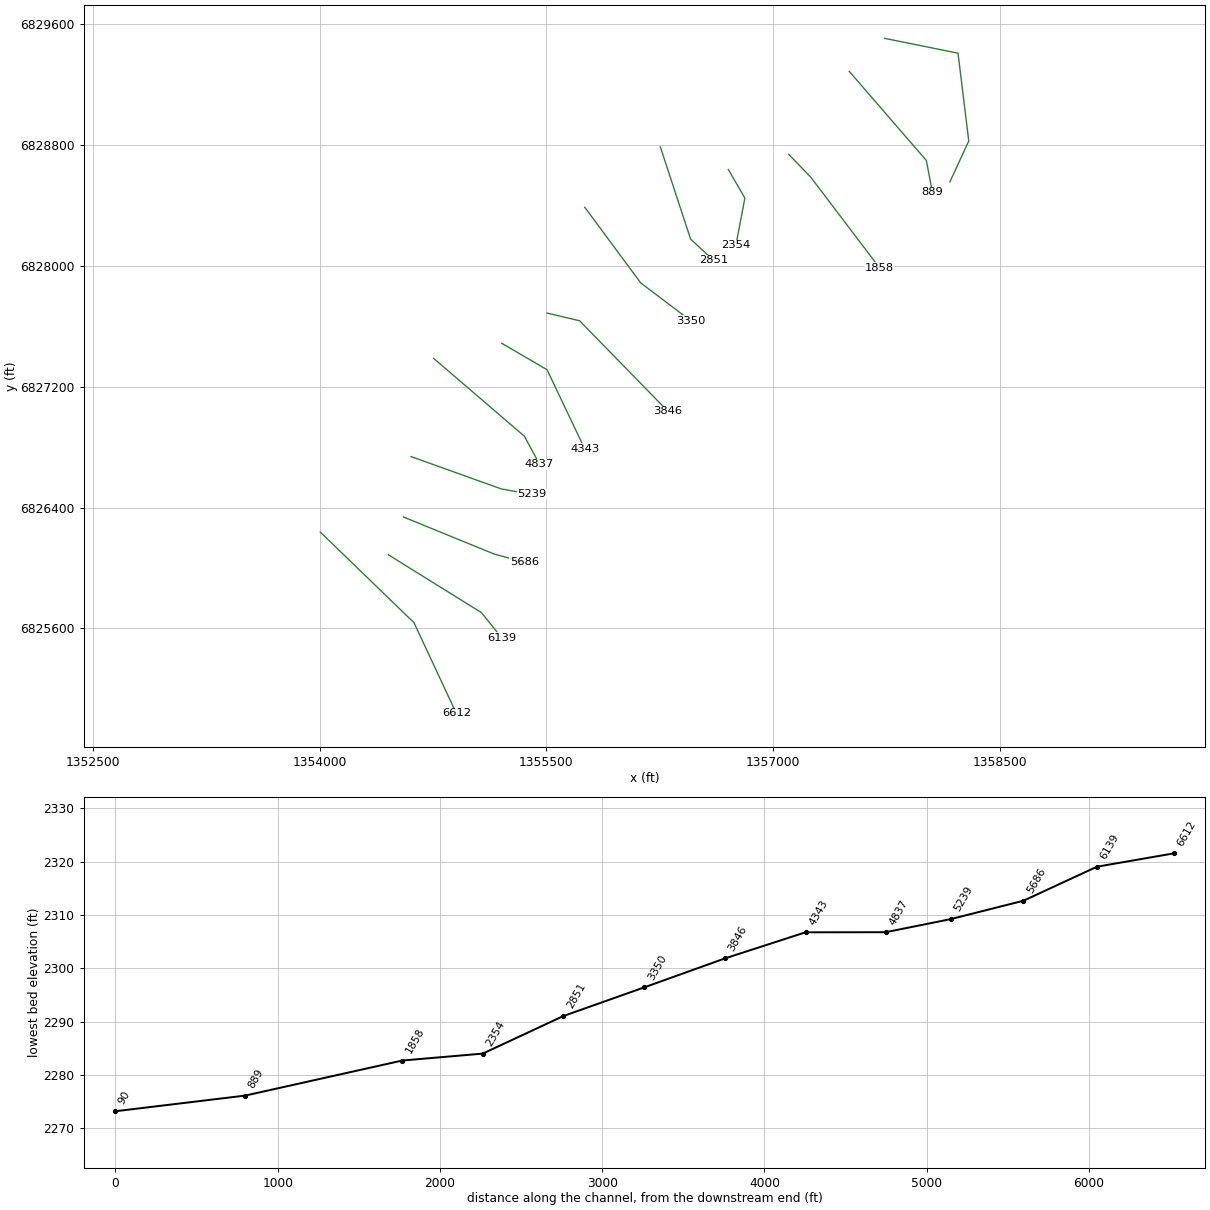
HEC-RAS study Seale Creek.prj: Seale Creek Base Level Engineering

--- Seale Creek.g01 (geometry) --- (continued)

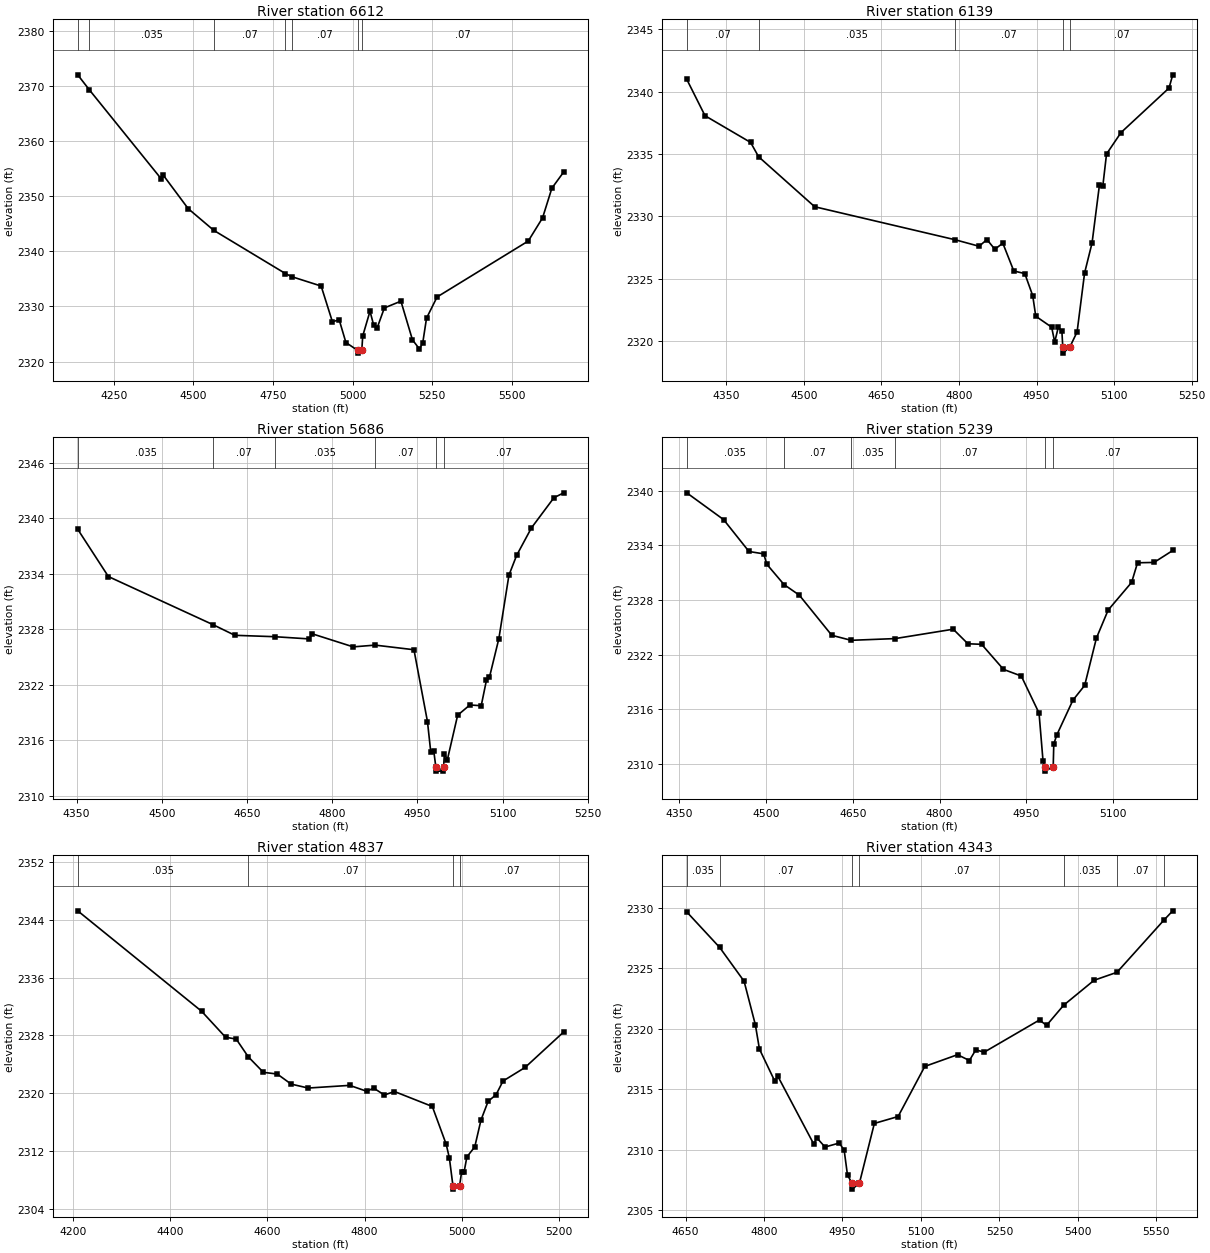
Type RM Length L Ch R = 1 ,6612    ,473,473,473
BEGIN DESCRIPTION:
Seale Creek 11.0
END DESCRIPTION:
XS GIS Cut Line= 3
      1354004.97      6826238.03      1354624.99      6825638.03
      1354905.02      6825037.96
#Sta/Elev= 30
  4137.2 2371.98  4173.7 2369.26    4399 2353.14  4405.9 2353.77  4483.9 2347.72
  4564.1 2343.79  4789.1 2335.95  4808.3  2335.4  4901.1 2333.69  4936.4 2327.22
  4957.7 2327.57  4978.8 2323.45  5015.6 2322.03  5016.1 2321.53  5028.6 2322.03
  5031.6 2324.65  5054.4 2329.13  5066.2 2326.54  5077.3 2326.17  5099.4 2329.72
  5151.4 2330.95  5187.6 2323.94  5209.7 2322.27    5220 2323.43  5231.8 2327.87
  5264.9 2331.71    5551 2341.85  5595.9 2346.05  5625.1 2351.43  5662.2 2354.37
#Mann= 7 ,-1 , 0
  4137.2     .07       0  4173.7    .035       0  4564.1     .07       0
  4789.1    .035       0  4808.3     .07       0  5015.6     .07       0
  5028.6     .07       0
Bank Sta=5015.6,5028.6
XS Rating Curve= 0 ,0
Exp/Cntr=0.3,0.1

Type RM Length L Ch R = 1 ,6139    ,453,453,453
BEGIN DESCRIPTION:
Seale Creek 10.0
END DESCRIPTION:
XS GIS Cut Line= 3
      1354454.99        6826088.      1355071.71      6825704.57
      1355204.98      6825538.02
#Sta/Elev= 30
  4273.8 2340.99  4309.1 2338.07  4397.2 2335.93  4412.7 2334.78  4521.1 2330.77
  4792.9 2328.12    4839  2327.6  4854.1 2328.14  4869.4 2327.36  4884.8 2327.85
    4906 2325.62  4927.3 2325.41  4942.6 2323.64  4948.5 2321.99  4979.2 2321.11
  4985.1 2319.92  4992.1 2321.11    4999 2320.79  5000.7 2319.53  5001.2 2319.03
  5014.5 2319.53  5028.4 2320.73  5042.9 2325.46  5057.3 2327.86  5071.7 2332.55
  5078.1 2332.42  5085.3    2335  5113.3 2336.72  5206.1 2340.29  5213.3 2341.35
#Mann= 5 ,-1 , 0
  4273.8     .07       0  4412.7    .035       0  4792.9     .07       0
  5000.7     .07       0  5014.5     .07       0
Bank Sta=5000.7,5014.5
XS Rating Curve= 0 ,0
Exp/Cntr=0.3,0.1

Type RM Length L Ch R = 1 ,5686    ,447,447,447
BEGIN DESCRIPTION:
Seale Creek 9.0
END DESCRIPTION:
XS GIS Cut Line= 3
      1354554.99        6826338.      1355154.91      6826093.04
      1355354.98      6826038.01
#Sta/Elev= 30
    4352 2338.79    4406 2333.68  4590.5 2328.47  4628.6 2327.33  4698.7 2327.18
  4759.5 2326.94  4764.9 2327.49    4837 2326.08  4875.6 2326.27  4943.9 2325.77
  4967.7    2318  4973.4 2314.77  4978.8 2314.82  4982.3 2313.15  4982.8 2312.65
  4995.7 2312.65  4996.2 2313.15  4997.4 2314.53  5002.7 2313.88  5020.8 2318.69
  5042.3  2319.8  5062.3 2319.72  5071.5 2322.47  5076.7 2322.77  5093.4 2326.98
  5111.1 2333.83  5124.6 2335.96  5150.7 2338.94  5190.3  2342.2  5207.5 2342.73
#Mann= 6 ,-1 , 0
    4352    .035       0  4590.5     .07       0  4698.7    .035       0
  4875.6     .07       0  4982.3     .07       0  4996.2     .07       0
Bank Sta=4982.3,4996.2
XS Rating Curve= 0 ,0
Exp/Cntr=0.3,0.1

Type RM Length L Ch R = 1 ,5239    ,402,402,402
BEGIN DESCRIPTION:
Seale Creek 8.0
END DESCRIPTION:
XS GIS Cut Line= 3
      1354605.01        6826738.      1355204.96      6826523.02
      1355405.02        6826488.
#Sta/Elev= 30
  4362.7 2339.76  4426.4 2336.82  4470.3 2333.32  4495.8 2333.06  4501.1 2331.92
  4530.9 2329.69  4557.3 2328.53  4613.5 2324.12  4646.9 2323.57  4723.1 2323.76
  4823.5 2324.79  4848.9 2323.19  4872.6 2323.13  4910.4 2320.38  4941.2 2319.65
  4971.9 2315.58  4978.8 2310.32  4982.5 2309.71    4983 2309.21  4996.4 2309.71
  4997.4 2312.19  5002.6 2313.18  5030.5    2317  5050.8 2318.62  5071.1 2323.81
  5091.4 2326.89    5132 2329.93  5142.2 2332.08  5170.8 2332.12  5203.1 2333.43
#Mann= 6 ,-1 , 0
  4362.7    .035       0  4530.9     .07       0  4646.9    .035       0
  4723.1     .07       0  4982.5     .07       0  4996.4     .07       0
Bank Sta=4982.5,4996.4
XS Rating Curve= 0 ,0
Exp/Cntr=0.3,0.1

Type RM Length L Ch R = 1 ,4837    ,494,494,494
BEGIN DESCRIPTION:
Seale Creek 7.0
END DESCRIPTION:
XS GIS Cut Line= 3
      1354755.01      6827387.99      1355355.19      6826872.92
      1355454.98      6826688.03
#Sta/Elev= 30
  4209.1 2345.24  4464.3 2331.35  4513.6 2327.76  4535.6  2327.5  4560.4 2325.05
  4591.6  2322.9  4620.1 2322.67  4648.6 2321.28  4683.7 2320.73  4769.3  2321.1
  4804.5 2320.28  4818.7 2320.72  4840.7 2319.77  4861.5 2320.25  4939.5 2318.18
    4968 2312.97  4974.6 2311.07  4981.9 2307.25  4982.4 2306.75  4995.8 2307.25
  4999.9 2309.18  5005.1 2309.18  5010.7 2311.21  5026.9 2312.59  5039.7  2316.3
  5054.5  2318.9  5070.7  2319.8  5085.1  2321.7  5130.6 2323.58  5210.1 2328.49
#Mann= 4 ,-1 , 0
  4209.1    .035       0  4560.4     .07       0  4981.9     .07       0
  4995.8     .07       0
Bank Sta=4981.9,4995.8
XS Rating Curve= 0 ,0
Exp/Cntr=0.3,0.1

Type RM Length L Ch R = 1 ,4343    ,497,497,497
BEGIN DESCRIPTION:
Seale Creek 6.0
END DESCRIPTION:
XS GIS Cut Line= 3
      1355204.97      6827488.02      1355505.31      6827313.04
      1355755.01      6826787.99
#Sta/Elev= 30
  4652.4 2329.64  4715.4  2326.7    4762 2323.91  4783.5 2320.32  4791.3 2318.31
  4820.8 2315.64  4826.6 2316.05  4895.2 2310.45    4901 2310.97  4916.7 2310.21
    4944 2310.54  4953.3 2309.94  4959.7 2307.88  4968.4 2307.23  4968.9 2306.73
  4982.5 2307.23    5011 2312.16  5056.4 2312.73  5107.4 2316.87    5170 2317.84
  5192.7 2317.36  5204.9 2318.24    5221 2318.05  5326.7 2320.71  5340.1 2320.26
  5372.9 2321.93    5431 2323.99  5474.8 2324.65  5565.1 2328.99  5581.4 2329.73
#Mann= 7 ,-1 , 0
  4652.4    .035       0  4715.4     .07       0  4968.4     .07       0
  4982.5     .07       0  5372.9    .035       0  5474.8     .07       0
  5565.1    .035       0
Bank Sta=4968.4,4982.5
XS Rating Curve= 0 ,0
Exp/Cntr=0.3,0.1

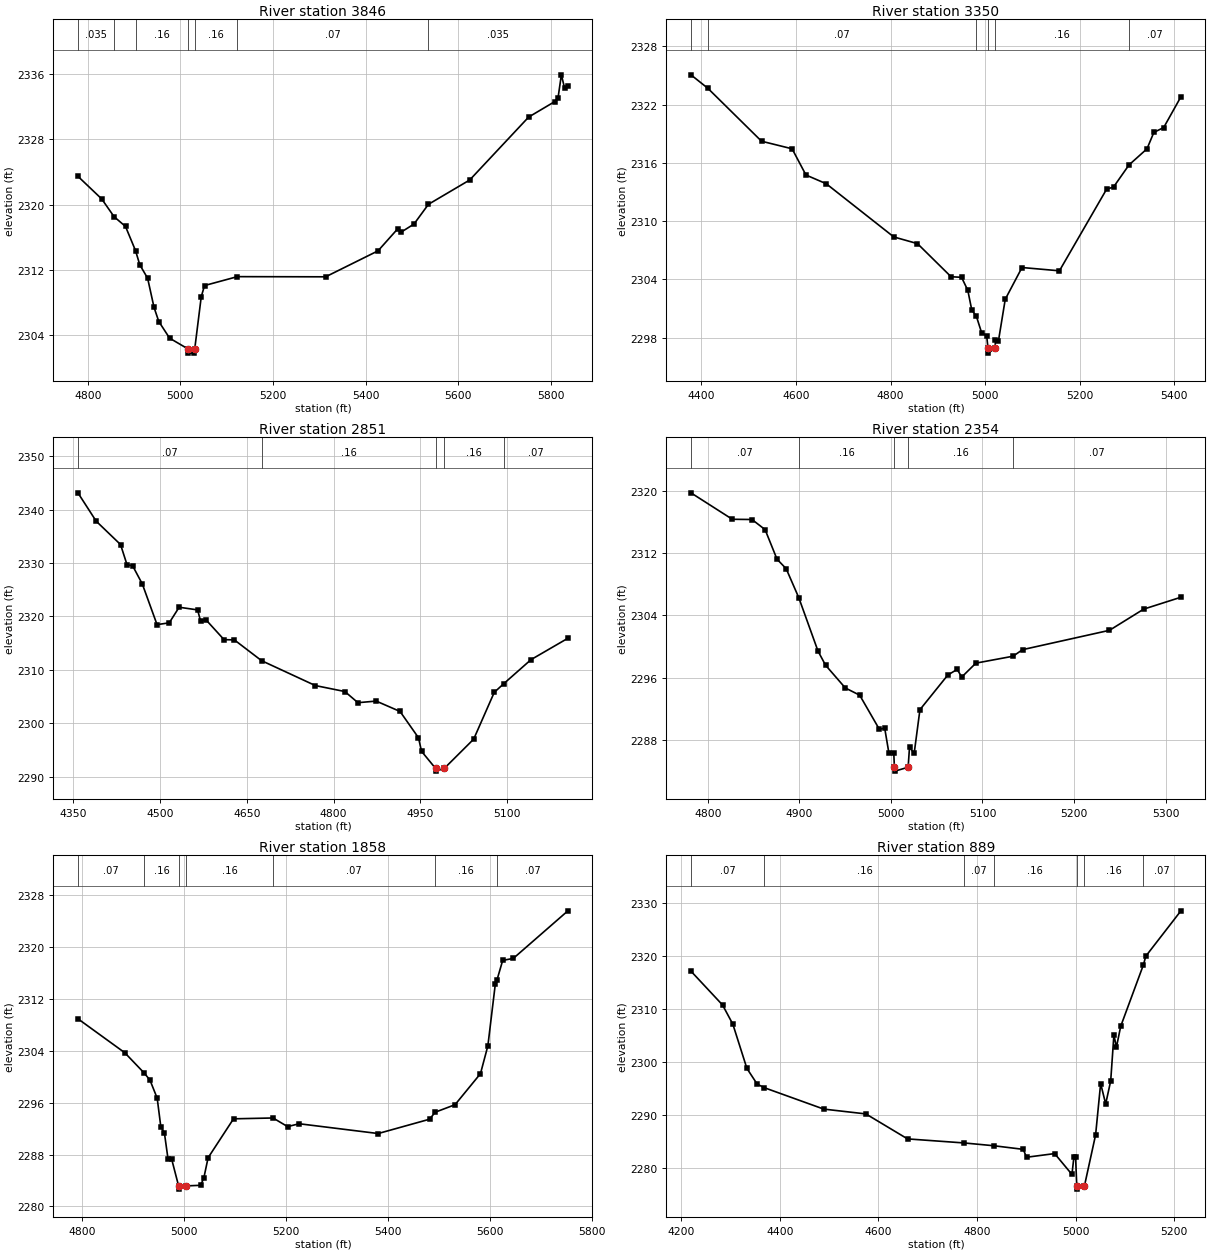
Type RM Length L Ch R = 1 ,3846    ,496,496,496
BEGIN DESCRIPTION:
Seale Creek 5.0
END DESCRIPTION:
XS GIS Cut Line= 3
      1355504.99        6827688.      1355720.36      6827637.12
      1356304.99      6827038.01
#Sta/Elev= 30
  4778.7 2323.47  4830.1  2320.7  4856.8 2318.53  4881.5 2317.33  4903.1 2314.38
  4912.3 2312.65  4929.3 2310.99  4943.1 2307.43  4953.4  2305.7  4976.8 2303.66
  5016.9 2302.33  5017.4 2301.83  5030.5 2301.83    5031 2302.33  5045.1 2308.73
  5052.2  2310.1  5123.1 2311.19  5313.8 2311.17    5427 2314.35  5469.4 2317.04
  5476.4 2316.62  5504.7 2317.63  5535.8 2320.04    5625 2323.02  5752.3 2330.72
  5808.9 2332.62  5815.9 2333.11    5823 2335.89    5830 2334.25  5837.1 2334.55
#Mann= 7 ,-1 , 0
  4778.7    .035       0  4856.8     .07       0  4903.1     .16       0
  5016.9     .07       0    5031     .16       0  5123.1     .07       0
  5535.8    .035       0
Bank Sta=5016.9,5031
XS Rating Curve= 0 ,0
Exp/Cntr=0.3,0.1

Type RM Length L Ch R = 1 ,3350    ,499,499,499
BEGIN DESCRIPTION:
Seale Creek 4.0
END DESCRIPTION:
XS GIS Cut Line= 3
      1355755.01      6828387.98      1356125.08       6827887.8
      1356454.99      6827638.01
#Sta/Elev= 30
  4377.8 2325.08  4413.4  2323.7  4527.1 2318.24  4591.7 2317.46    4621 2314.76
  4663.9 2313.86  4806.7 2308.38  4856.8 2307.69  4927.8 2304.28    4950 2304.22
  4963.2 2302.88  4971.6 2300.85  4981.3 2300.21  4992.5  2298.5  5003.1  2298.2
  5005.9 2296.91  5006.4 2296.41  5020.8 2296.91  5021.6 2297.74  5027.9 2297.64
  5042.4 2301.96  5077.8 2305.23  5156.9 2304.89  5256.7  2313.3  5271.3 2313.52
  5304.1  2315.8  5342.1 2317.46  5356.6 2319.15  5377.4 2319.65  5413.8 2322.82
#Mann= 6 ,-1 , 0
  4377.8    .035       0  4413.4     .07       0  4981.3     .16       0
  5005.9     .07       0  5020.8     .16       0  5304.1     .07       0
Bank Sta=5005.9,5020.8
XS Rating Curve= 0 ,0
Exp/Cntr=0.3,0.1

Type RM Length L Ch R = 1 ,2851    ,497,497,497
BEGIN DESCRIPTION:
Seale Creek 3.0
END DESCRIPTION:
XS GIS Cut Line= 3
        1356255.        6828788.      1356455.17      6828177.89
      1356605.01      6828037.99
#Sta/Elev= 30
  4357.9 2343.16  4389.5 2337.85  4431.6 2333.47  4442.7 2329.72  4452.6 2329.47
  4469.3 2326.07  4494.7 2318.47  4515.8 2318.81  4532.9 2321.73  4564.8 2321.23
    4570 2319.13  4578.9 2319.42  4610.5 2315.66  4628.4 2315.61  4675.4 2311.72
  4768.3 2307.06  4819.4 2305.94    4842 2303.85  4873.6 2304.15  4914.8 2302.21
  4946.7 2297.28  4951.9 2294.75  4976.3 2291.53  4976.8 2291.03  4991.2 2291.53
  5042.1 2297.02  5077.7 2305.79  5093.9 2307.39  5141.2 2311.91    5205 2315.92
#Mann= 5 ,-1 , 0
  4357.9     .07       0  4675.4     .16       0  4976.3     .07       0
  4991.2     .16       0  5093.9     .07       0
Bank Sta=4976.3,4991.2
XS Rating Curve= 0 ,0
Exp/Cntr=0.3,0.1

Type RM Length L Ch R = 1 ,2354    ,496,496,496
BEGIN DESCRIPTION:
Seale Creek 2.0
END DESCRIPTION:
XS GIS Cut Line= 3
      1356704.98      6828638.03      1356814.54       6828449.1
      1356755.01      6828138.05
#Sta/Elev= 30
  4781.6 2319.75  4826.8 2316.35  4848.3 2316.32  4862.6 2315.02  4875.6 2311.22
  4885.6    2310  4899.4 2306.27  4920.4  2299.4  4928.6  2297.6  4950.2 2294.67
  4965.9 2293.74  4987.4 2289.35  4993.2 2289.51  4997.7 2286.37  5003.1 2286.37
  5003.8 2284.48  5004.3 2283.98  5018.8 2284.48  5020.3 2287.04  5025.4 2286.27
  5031.7 2291.88  5062.2 2296.34  5072.3 2297.05  5077.4 2296.08  5092.8 2297.86
  5133.4 2298.75  5143.7 2299.59  5238.7 2302.08    5276  2304.8  5316.7 2306.33
#Mann= 5 ,-1 , 0
  4781.6     .07       0  4899.4     .16       0  5003.8     .07       0
  5018.8     .16       0  5133.4     .07       0
Bank Sta=5003.8,5018.8
XS Rating Curve= 0 ,0
Exp/Cntr=0.3,0.1

Type RM Length L Ch R = 1 ,1858    ,969,969,969
BEGIN DESCRIPTION:
Seale Creek 1.0
END DESCRIPTION:
XS GIS Cut Line= 3
      1357104.97      6828738.03      1357249.88      6828588.12
      1357705.01      6827987.99
#Sta/Elev= 30
  4791.5 2308.97  4883.5 2303.73  4921.8 2300.58  4932.9 2299.51  4947.1 2296.71
  4954.3 2292.25  4961.2 2291.38  4968.4 2287.31  4975.4 2287.34  4989.1 2283.18
  4989.6 2282.68  5004.1 2283.18  5032.4 2283.27  5038.7 2284.43    5047 2287.52
  5096.9 2293.53  5174.5 2293.66    5203 2292.33  5225.8 2292.77  5380.8 2291.26
  5481.7 2293.47  5492.7 2294.55  5531.7 2295.71  5581.6  2300.5  5596.1 2304.79
  5610.7 2314.31  5613.8  2314.9  5625.2 2317.98  5646.1 2318.29  5753.2 2325.63
#Mann= 7 ,-1 , 0
  4791.5     .07       0  4921.8     .16       0  4989.1     .07       0
  5004.1     .16       0  5174.5     .07       0  5492.7     .16       0
  5613.8     .07       0
Bank Sta=4989.1,5004.1
XS Rating Curve= 0 ,0
Exp/Cntr=0.3,0.1

Type RM Length L Ch R = 1 ,889     ,799,799,799
BEGIN DESCRIPTION:
Sweetwater Creek Trib 41T2 12.0
END DESCRIPTION:
XS GIS Cut Line= 3
      1357505.02      6829287.98       1358015.3      6828697.92
      1358054.99      6828488.04
#Sta/Elev= 30
  4219.9  2317.2    4284 2310.82  4304.9  2307.2  4333.4 2298.86  4354.3 2295.89
  4369.1 2295.21  4489.2 2291.19  4574.7 2290.28  4659.2 2285.57  4774.7  2284.8
  4834.2 2284.28  4893.8  2283.6  4900.5 2282.11  4957.5  2282.8  4992.6 2278.87
  4996.6 2282.18    5000 2282.18  5002.4  2276.6  5002.9  2276.1  5017.7  2276.6
  5040.6 2286.34  5050.8 2296.01    5061 2292.16  5071.2 2296.51  5077.7 2305.17
  5082.8 2302.86  5091.5  2306.8  5137.6  2318.4  5142.4 2320.02  5213.6 2328.57
#Mann= 7 ,-1 , 0
  4219.9     .07       0  4369.1     .16       0  4774.7     .07       0
  4834.2     .16       0  5002.4     .07       0  5017.7     .16       0
  5137.6     .07       0
Bank Sta=5002.4,5017.7
XS Rating Curve= 0 ,0
Exp/Cntr=0.3,0.1

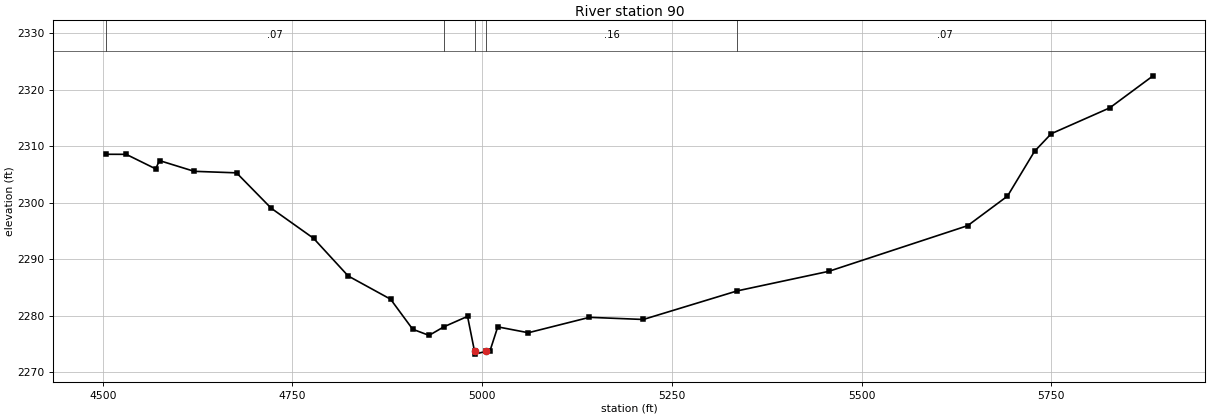
Type RM Length L Ch R = 1 ,90      ,0,0,0
BEGIN DESCRIPTION:
Seale Creek 4356
END DESCRIPTION:
XS GIS Cut Line= 4
      1357738.62      6829506.65      1358224.78      6829408.35
      1358295.91      6828826.96      1358170.92      6828556.14
#Sta/Elev= 30
    4504 2308.58  4530.9 2308.57  4569.7    2306  4574.8 2307.46  4620.5 2305.56
  4676.3 2305.29    4722 2299.02  4777.8 2293.69  4823.4 2287.02  4879.3  2282.9
  4908.4 2277.58    4930 2276.49  4949.5 2278.01  4980.7 2279.86  4989.9 2273.67
  4990.4 2273.17  5005.3 2273.67  5010.4  2273.8  5020.5    2278  5060.8 2276.96
  5141.4 2279.69  5212.3 2279.31  5336.2 2284.38  5456.7 2287.84  5639.7 2295.93
  5692.2 2301.17  5727.8  2309.1  5749.8 2312.22  5826.9  2316.8    5884 2322.48
#Mann= 5 ,-1 , 0
    4504     .07       0  4949.5     .16       0  4989.9     .07       0
  5005.3     .16       0  5336.2     .07       0
Bank Sta=4989.9,5005.3
XS Rating Curve= 0 ,0
Exp/Cntr=0.3,0.1

Chan Stop Cuts=-1
Use User Specified Reach Order=0
Composite Channel Slope=5