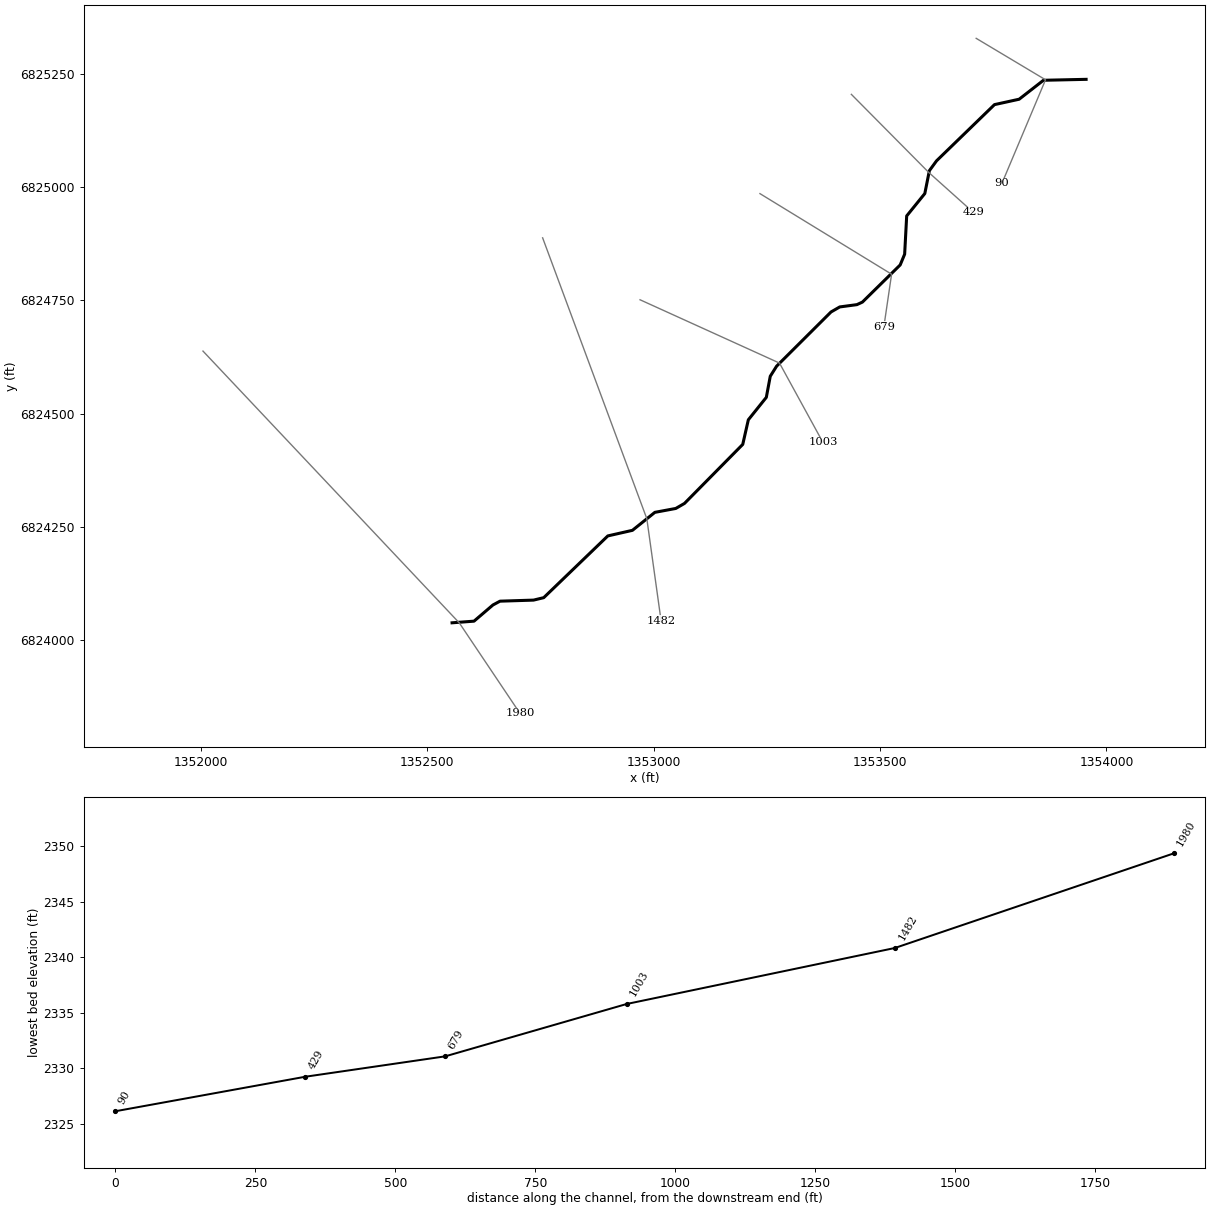
--- Seale Creek Trib1.prj (project) ---

Proj Title=Seale Creek Trib1 Base Level Engineering
Current Plan=p01
Default Exp/Contr=0.3,0.1
English Units
Geom File=g01
Flow File=f01
Plan File=p01
Y Axis Title=Elevation
X Axis Title(PF)=Main Channel Distance
X Axis Title(XS)=Station
BEGIN DESCRIPTION:
Seale Creek Trib1
END DESCRIPTION:
DSS Export Rating Curves= 0
DSS Export Rating Curve Sorted= 0
DSS Export Volume Flow Curves= 0
DXF OffsetX= 0
DXF OffsetY= 0
DXF ScaleX= 1
DXF ScaleY= 10

--- Seale Creek Trib1.p01 (plan) ---

Plan Title=Multiple Run
Short Identifier=Multiple
Geom File=g01
Flow File=f01
Subcritical Flow
K Sum by GR= 0
Std Step Tol= 0.01
Critical Tol= 0.01
Num of Std Step Trials= 20
Max Error Tol= 0.3
Flow Tol Ratio= 0.001
Split Flow NTrial= 30
Split Flow Tol= 0.02
Split Flow Ratio= 0.02
Log Output Level= 0
Friction Slope Method= 1
Unsteady Friction Slope Method= 2
Unsteady Bridges Friction Slope Method= 1
Parabolic Critical Depth
Global Vel Dist=  1 , 1 , 1
Global Log Level= 0
CheckData=True
Encroach Param= -1, 0, 0, 0
BEGIN DESCRIPTION:
Multiple Run
END DESCRIPTION:

--- Seale Creek Trib1.f01 (steady flow) ---

Flow Title=Multiple
Number of Profiles=7
Profile Names=10-year,25-year,50-year,1pct_min,100-year,1pct_plu,500-year
River Rch & RM= Seale Creek Trib,Reach-1,1980
     318     460     583     367     733    1462    1174
River Rch & RM= Seale Creek Trib,Reach-1,679
     316     457     579     364     727    1450    1162
Boundary for River Rch & Prof#=Seale Creek Trib,Reach-1,1
Up Type=0
Dn Type=3
Dn Slope=0.005
Boundary for River Rch & Prof#=Seale Creek Trib,Reach-1,2
Up Type=0
Dn Type=3
Dn Slope=0.005
Boundary for River Rch & Prof#=Seale Creek Trib,Reach-1,3
Up Type=0
Dn Type=3
Dn Slope=0.005
Boundary for River Rch & Prof#=Seale Creek Trib,Reach-1,4
Up Type=0
Dn Type=3
Dn Slope=0.005
Boundary for River Rch & Prof#=Seale Creek Trib,Reach-1,5
Up Type=0
Dn Type=3
Dn Slope=0.005
Boundary for River Rch & Prof#=Seale Creek Trib,Reach-1,6
Up Type=0
Dn Type=3
Dn Slope=0.005
Boundary for River Rch & Prof#=Seale Creek Trib,Reach-1,7
Up Type=0
Dn Type=3
Dn Slope=0.005

--- Seale Creek Trib1.g01 (geometry) ---

Geom Title=Existing Conditions

River Reach=Seale Creek Trib,Reach-1
Reach XY= 30
      1352555.00      6824038.00      1352603.49      6824041.64
      1352645.26      6824077.38      1352660.92      6824085.77
      1352734.95      6824088.12      1352757.43      6824093.52
      1352898.94      6824229.86      1352953.26      6824242.19
      1353002.81      6824281.90      1353048.97      6824290.50
      1353068.22      6824301.62      1353196.86      6824431.94
      1353209.19      6824486.26      1353248.90      6824535.81
      1353257.61      6824582.37      1353271.64      6824604.68
      1353391.79      6824724.37      1353411.05      6824735.46
      1353448.96      6824740.53      1353461.07      6824746.15
      1353544.49      6824828.19      1353554.33      6824851.91
      1353558.83      6824936.41      1353598.86      6824985.83
      1353608.94      6825036.37      1353624.78      6825058.09
      1353752.70      6825182.17      1353807.18      6825194.11
      1353860.86      6825235.93      1353955.00      6825238.00

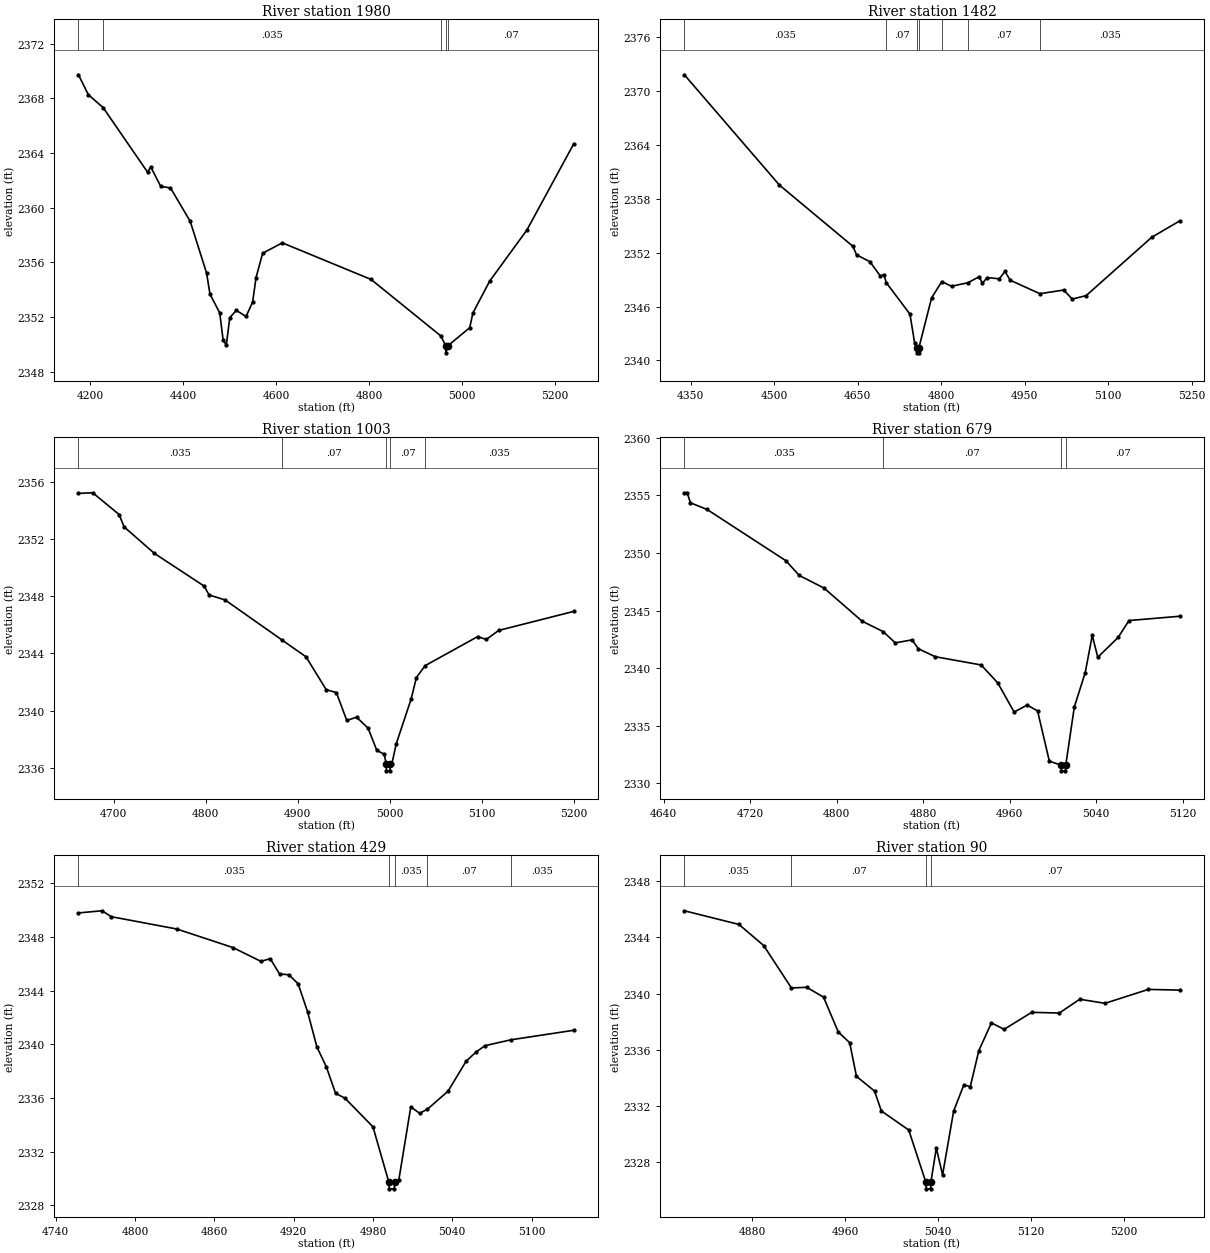
Type RM Length L Ch R = 1,1980,498,498,498
BEGIN DESCRIPTION:
Seale Creek Trib1 1.0
END DESCRIPTION:
XS GIS Cut Line= 3
      1352005.02      6824637.98      1352571.14      6824037.59
      1352704.99      6823838.02
#Sta/Elev= 30
  4174.8 2369.72  4196.0 2368.26  4227.8 2367.32  4323.5 2362.59  4330.3 2362.98
  4351.8 2361.55  4372.8 2361.44  4415.3 2358.99  4450.5 2355.20  4457.8 2353.66
  4478.8 2352.29  4486.1 2350.29  4493.0 2349.95  4500.3 2351.94  4514.4 2352.48
  4535.4 2352.03  4549.6 2353.09  4556.9 2354.88  4571.1 2356.66  4613.5 2357.42
  4804.5 2354.74  4954.8 2350.60  4965.1 2349.87  4965.4 2349.37  4969.1 2349.87
  5016.7 2351.21  5023.6 2352.29  5059.7 2354.62  5139.8 2358.36  5240.3 2364.65
#Mann=5,-1,0
  4174.8    0.07       0  4227.8   0.035       0  4954.8    0.07       0
  4965.1    0.07       0  4969.1    0.07       0
Bank Sta=4965.1,4969.1
Exp/Cntr=0.3,0.1

Type RM Length L Ch R = 1,1482,479,479,479
BEGIN DESCRIPTION:
Bitter Creek Trib1T2_1 13.0
END DESCRIPTION:
XS GIS Cut Line= 3
      1352754.99      6824888.02      1352985.07      6824267.82
      1353016.62      6824041.92
#Sta/Elev= 30
  4338.5 2371.83  4509.2 2359.54  4641.5 2352.70  4647.8 2351.76  4671.8 2351.00
  4690.5 2349.41  4696.9 2349.55  4701.4 2348.65  4743.8 2345.15  4752.3 2341.91
  4755.6 2341.34  4755.9 2340.84  4759.4 2340.84  4759.6 2341.34  4782.7 2346.97
  4801.0 2348.78  4818.5 2348.26  4847.8 2348.65  4868.4 2349.33  4873.8 2348.58
  4882.5 2349.23  4904.2 2349.09  4914.5 2349.91  4923.9 2348.93  4977.3 2347.43
  5020.0 2347.84  5035.4 2346.83  5060.4 2347.22  5178.4 2353.73  5228.1 2355.53
#Mann=7,-1,0
  4338.5   0.035       0  4701.4    0.07       0  4755.6   0.035       0
  4759.6    0.07       0  4801.0   0.035       0  4847.8    0.07       0
  4977.3   0.035       0
Bank Sta=4755.6,4759.6
Exp/Cntr=0.3,0.1

Type RM Length L Ch R = 1,1003,324,324,324
BEGIN DESCRIPTION:
Seale Creek Trib1 4357
END DESCRIPTION:
XS GIS Cut Line= 3
      1352970.07      6824751.29      1353278.01      6824611.47
      1353373.77      6824436.57
#Sta/Elev= 30
  4661.8 2355.18  4677.3 2355.22  4705.9 2353.70  4711.3 2352.84  4744.1 2350.99
  4798.2 2348.70  4803.6 2348.08  4821.0 2347.73  4882.6 2344.94  4908.8 2343.76
  4930.8 2341.46  4941.8 2341.26  4953.1 2339.31  4963.7 2339.54  4976.2 2338.78
  4985.7 2337.22  4993.8 2336.95  4995.9 2336.29  4996.2 2335.79  5000.0 2335.79
  5000.3 2336.29  5002.1 2336.29  5006.9 2337.70  5023.0 2340.81  5028.7 2342.31
  5038.2 2343.14  5095.2 2345.17  5104.6 2344.97  5118.0 2345.60  5199.4 2346.93
#Mann=5,-1,0
  4661.8   0.035       0  4882.6    0.07       0  4995.9    0.07       0
  5000.3    0.07       0  5038.2   0.035       0
Bank Sta=4995.9,5000.3
Exp/Cntr=0.3,0.1

Type RM Length L Ch R = 1,679,250,250,250
BEGIN DESCRIPTION:
Seale Creek Trib1 4358
END DESCRIPTION:
XS GIS Cut Line= 3
      1353234.85      6824985.66      1353525.51      6824807.73
      1353508.48      6824691.77
#Sta/Elev= 30
  4659.2 2355.23  4661.8 2355.23  4664.8 2354.36  4680.2 2353.78  4753.2 2349.32
  4765.4 2348.05  4788.4 2346.95  4823.5 2344.08  4843.0 2343.17  4854.3 2342.19
  4869.8 2342.45  4875.6 2341.68  4891.1 2340.99  4933.7 2340.27  4949.1 2338.71
  4964.2 2336.18  4976.3 2336.78  4985.9 2336.28  4996.8 2331.91  5007.6 2331.57
  5007.9 2331.07  5011.7 2331.07  5012.0 2331.57  5019.9 2336.62  5030.0 2339.61
  5036.5 2342.84  5041.6 2340.94  5060.4 2342.66  5070.5 2344.13  5117.2 2344.50
#Mann=4,-1,0
  4659.2   0.035       0  4843.0    0.07       0  5007.6    0.07       0
  5012.0    0.07       0
Bank Sta=5007.6,5012
Exp/Cntr=0.3,0.1

Type RM Length L Ch R = 1,429,339,339,339
BEGIN DESCRIPTION:
Seale Creek Trib1 4359
END DESCRIPTION:
XS GIS Cut Line= 3
      1353436.69      6825204.83      1353607.61      6825032.38
      1353705.77      6824944.43
#Sta/Elev= 30
  4757.2 2349.80  4775.0 2349.96  4782.0 2349.52  4831.6 2348.60  4874.0 2347.22
  4895.2 2346.19  4902.3 2346.39  4909.3 2345.25  4916.4 2345.19  4923.4 2344.51
  4930.5 2342.44  4937.6 2339.80  4944.7 2338.33  4951.7 2336.35  4958.8 2335.99
  4980.0 2333.85  4992.0 2329.73  4992.3 2329.23  4996.1 2329.23  4996.4 2329.73
  4999.6 2329.92  5008.6 2335.34  5015.3 2334.86  5021.2 2335.17  5036.8 2336.51
  5050.5 2338.75  5058.0 2339.43  5064.7 2339.90  5084.3 2340.34  5131.8 2341.05
#Mann=5,-1,0
  4757.2   0.035       0  4992.0   0.035       0  4996.4   0.035       0
  5021.2    0.07       0  5084.3   0.035       0
Bank Sta=4992,4996.4
Exp/Cntr=0.3,0.1

Type RM Length L Ch R = 1,90,0,0,0
BEGIN DESCRIPTION:
Seale Creek Trib1 4360
END DESCRIPTION:
XS GIS Cut Line= 3
      1353712.29      6825328.54      1353865.41      6825237.00
      1353769.37      6825008.90
#Sta/Elev= 30
  4821.6 2345.89  4868.5 2344.92  4889.8 2343.42  4913.7 2340.40  4926.8 2340.45
  4941.3 2339.75  4954.0 2337.27  4963.8 2336.51  4969.6 2334.12  4985.2 2333.07
  4991.0 2331.66  5014.6 2330.30  5029.2 2326.62  5029.6 2326.12  5033.4 2326.12
  5033.7 2326.62  5038.3 2329.02  5043.7 2327.11  5053.2 2331.64  5062.0 2333.52
  5067.5 2333.38  5074.9 2335.95  5085.7 2337.92  5096.6 2337.46  5120.4 2338.67
  5144.1 2338.62  5161.7 2339.60  5183.4 2339.31  5220.7 2340.30  5247.5 2340.25
#Mann=4,-1,0
  4821.6   0.035       0  4913.7    0.07       0  5029.2    0.07       0
  5033.7    0.07       0
Bank Sta=5029.2,5033.7
Exp/Cntr=0.3,0.1

Chan Stop Cuts=-1