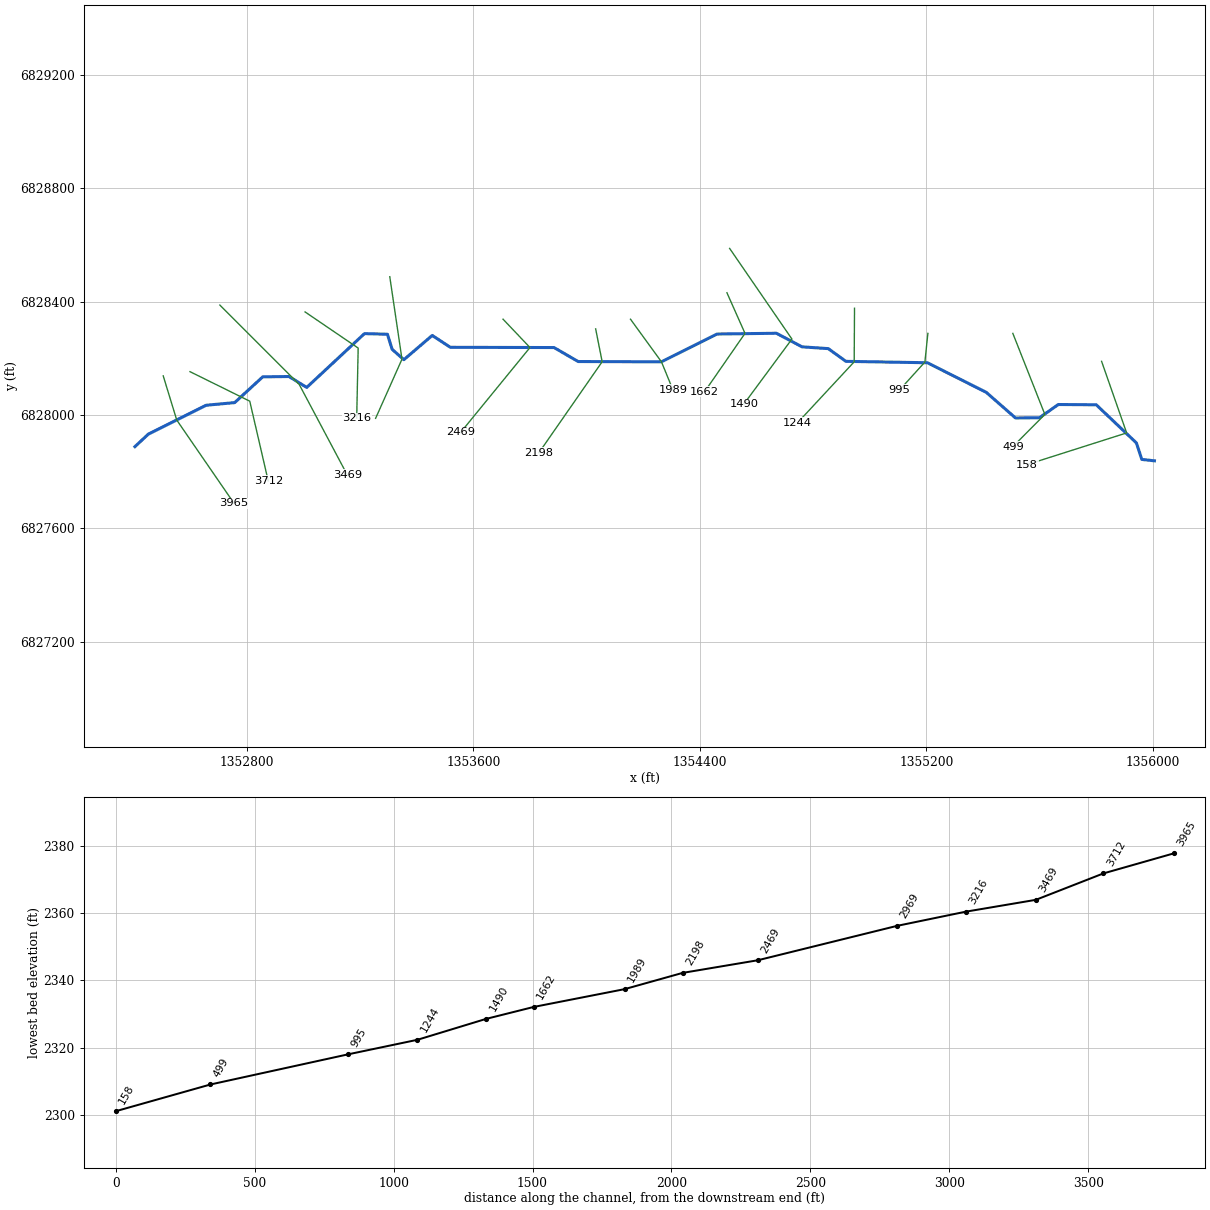
--- Seale Creek Trib2.prj (project) ---

Proj Title=Seale Creek Trib2 Base Level Engineering
Current Plan=p01
Default Exp/Contr=0.3,0.1
English Units
Geom File=g01
Flow File=f01
Plan File=p01
Y Axis Title=Elevation
X Axis Title(PF)=Main Channel Distance
X Axis Title(XS)=Station
BEGIN DESCRIPTION:
Seale Creek Trib2
END DESCRIPTION:
DSS Export Rating Curves= 0
DSS Export Rating Curve Sorted= 0
DSS Export Volume Flow Curves= 0
DXF OffsetX= 0
DXF OffsetY= 0
DXF ScaleX= 1
DXF ScaleY= 10

--- Seale Creek Trib2.p01 (plan) ---

Plan Title=Multiple Run
Short Identifier=Multiple
Geom File=g01
Flow File=f01
Subcritical Flow
K Sum by GR= 0
Std Step Tol= 0.01
Critical Tol= 0.01
Num of Std Step Trials= 20
Max Error Tol= 0.3
Flow Tol Ratio= 0.001
Split Flow NTrial= 30
Split Flow Tol= 0.02
Split Flow Ratio= 0.02
Log Output Level= 0
Friction Slope Method= 1
Unsteady Friction Slope Method= 2
Unsteady Bridges Friction Slope Method= 1
Parabolic Critical Depth
Global Vel Dist=  1 , 1 , 1
Global Log Level= 0
CheckData=True
Encroach Param= -1, 0, 0, 0
BEGIN DESCRIPTION:
Multiple Run
END DESCRIPTION:

--- Seale Creek Trib2.f01 (steady flow) ---

Flow Title=Multiple
Number of Profiles=7
Profile Names=10-year,25-year,50-year,1pct_min,100-year,1pct_plu,500-year
River Rch & RM= Seale Creek Trib,Reach-1,3965
     147     205     252     155     309     617     471
Boundary for River Rch & Prof#=Seale Creek Trib,Reach-1,1
Up Type=0
Dn Type=3
Dn Slope=0.005
Boundary for River Rch & Prof#=Seale Creek Trib,Reach-1,2
Up Type=0
Dn Type=3
Dn Slope=0.005
Boundary for River Rch & Prof#=Seale Creek Trib,Reach-1,3
Up Type=0
Dn Type=3
Dn Slope=0.005
Boundary for River Rch & Prof#=Seale Creek Trib,Reach-1,4
Up Type=0
Dn Type=3
Dn Slope=0.005
Boundary for River Rch & Prof#=Seale Creek Trib,Reach-1,5
Up Type=0
Dn Type=3
Dn Slope=0.005
Boundary for River Rch & Prof#=Seale Creek Trib,Reach-1,6
Up Type=0
Dn Type=3
Dn Slope=0.005
Boundary for River Rch & Prof#=Seale Creek Trib,Reach-1,7
Up Type=0
Dn Type=3
Dn Slope=0.005

--- Seale Creek Trib2.g01 (geometry) ---

Geom Title=Existing Conditions
Program Version=4.10

River Reach=Seale Creek Trib,Reach-1
Reach XY= 30
        1352405.        6827888.      1352452.64      6827932.33
      1352656.59      6828034.17      1352757.42      6828043.54
       1352856.5      6828134.53      1352949.11      6828135.63
      1353011.74      6828097.13      1353215.59      6828287.11
      1353296.66      6828284.98       1353313.3      6828231.64
       1353354.8      6828195.04       1353454.9      6828280.66
      1353518.86      6828238.83      1353884.97      6828237.93
      1353970.22      6828188.52      1354264.28      6828187.55
      1354460.52      6828285.65      1354670.18      6828288.43
      1354760.57      6828240.47       1354853.4      6828234.14
       1354915.5      6828189.22      1355203.45      6828184.25
      1355411.05      6828079.84      1355514.64       6827989.1
      1355599.02      6827990.16      1355665.51      6828036.79
      1355799.55      6828035.84       1355941.4      6827901.08
      1355960.33      6827842.92        1356005.        6827838.

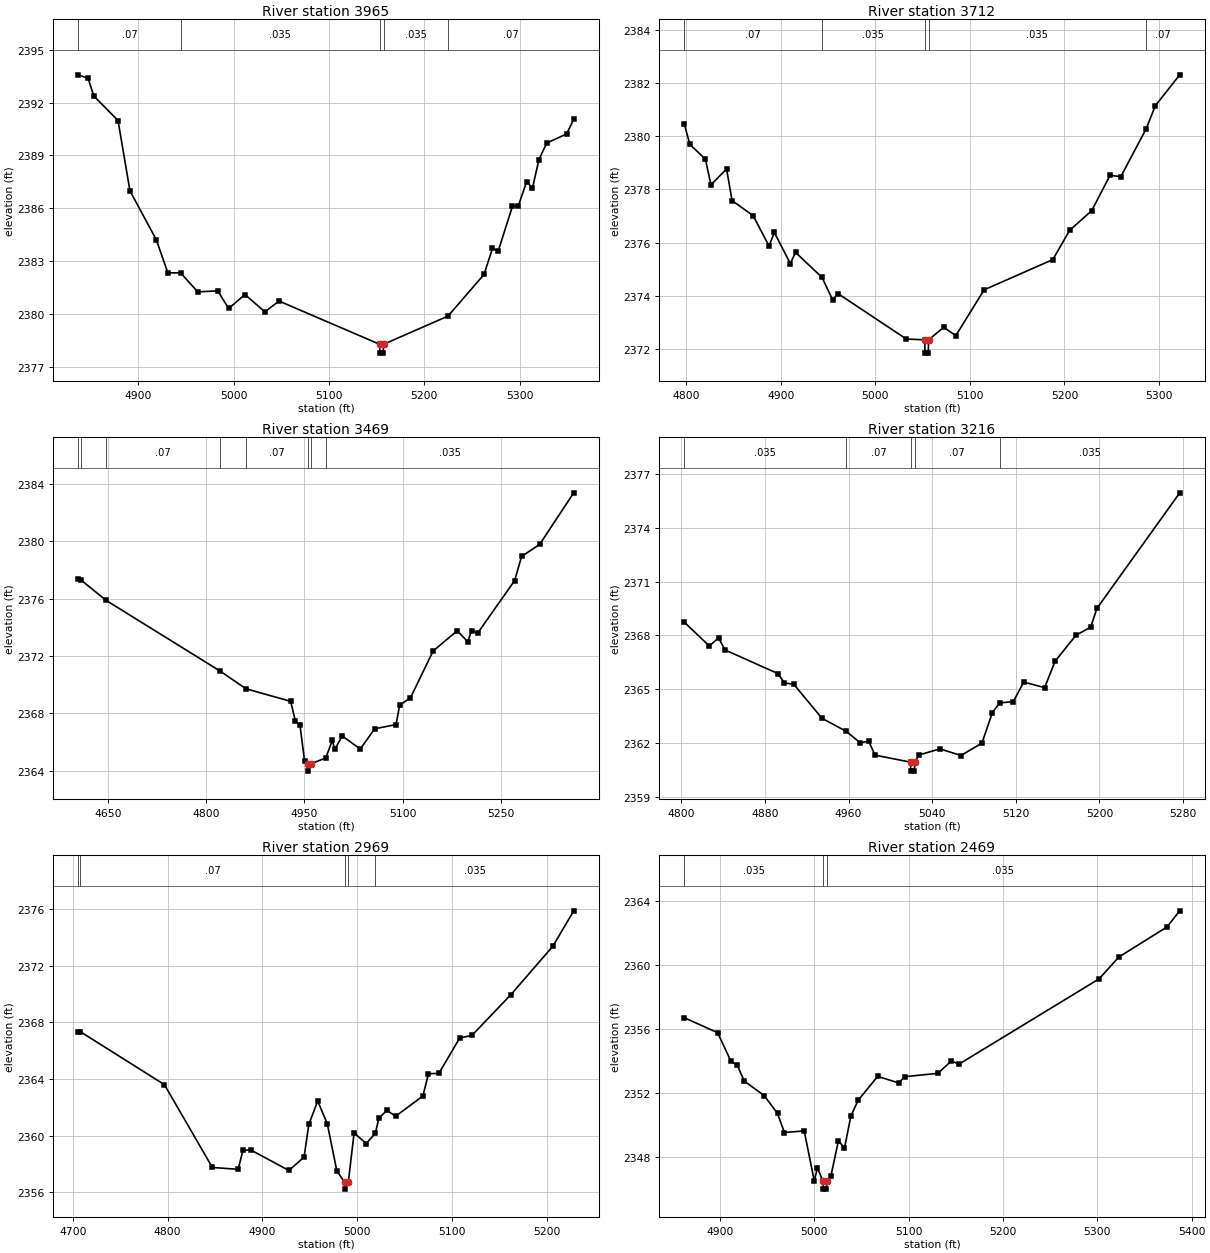
Type RM Length L Ch R = 1 ,3965    ,253,253,253
BEGIN DESCRIPTION:
Seale Creek Trib2 7.0
END DESCRIPTION:
XS GIS Cut Line= 3
      1352505.01      6828137.98       1352552.8      6827981.93
      1352755.02      6827687.97
#Sta/Elev= 30
  4836.8 2393.57  4847.2 2393.37  4853.2 2392.37  4878.6 2390.98  4891.1    2387
  4918.7 2384.23  4930.9 2382.35  4944.2 2382.35  4962.3 2381.27  4983.2 2381.33
  4994.7 2380.33  5011.8 2381.12  5032.7 2380.14  5047.6 2380.75  5153.2  2378.3
  5153.4  2377.8  5156.9  2377.8  5157.2  2378.3  5224.9  2379.9  5262.7 2382.26
  5271.5 2383.73  5277.6 2383.59  5292.5 2386.12  5298.6 2386.13  5307.4 2387.52
  5313.5 2387.15  5320.3 2388.77  5328.4  2389.7  5349.3 2390.22  5356.8 2391.05
#Mann= 5 ,-1 , 0
  4836.8     .07       0  4944.2    .035       0  5153.2    .035       0
  5157.2    .035       0  5224.9     .07       0
Bank Sta=5153.2,5157.2
XS Rating Curve= 0 ,0
Exp/Cntr=0.3,0.1

Type RM Length L Ch R = 1 ,3712    ,243,243,243
BEGIN DESCRIPTION:
Seale Creek Trib2 4362
END DESCRIPTION:
XS GIS Cut Line= 3
      1352599.64      6828152.76      1352810.59      6828048.59
       1352875.7      6827767.29
#Sta/Elev= 30
  4797.9 2380.47  4803.9 2379.69  4820.3 2379.14  4826.2 2378.17  4842.7 2378.77
  4848.5 2377.58  4870.8 2377.01  4887.6 2375.87  4893.2 2376.38  4910.1 2375.21
  4915.6 2375.63  4943.6 2374.69  4954.9 2373.84  4960.5 2374.08  5032.8 2372.37
  5052.3 2372.34  5052.5 2371.84    5056 2371.84  5056.3 2372.34  5072.3 2372.81
  5085.1  2372.5    5115 2374.22  5187.7 2375.36  5205.5 2376.46  5228.8  2377.2
  5248.2 2378.53  5259.6 2378.48  5286.4 2380.28  5296.1 2381.15  5321.9 2382.31
#Mann= 5 ,-1 , 0
  4797.9     .07       0  4943.6    .035       0  5052.3    .035       0
  5056.3    .035       0  5286.4     .07       0
Bank Sta=5052.3,5056.3
XS Rating Curve= 0 ,0
Exp/Cntr=0.3,0.1

Type RM Length L Ch R = 1 ,3469    ,253,253,253
BEGIN DESCRIPTION:
Seale Creek Trib2 6.0
END DESCRIPTION:
XS GIS Cut Line= 3
      1352705.02      6828387.98       1352985.2      6828107.71
        1353155.      6827788.01
#Sta/Elev= 30
  4603.7 2377.34  4607.9 2377.29  4646.4 2375.87  4820.8 2370.95  4860.6 2369.71
  4928.9 2368.84    4936 2367.47  4943.1 2367.17  4950.2 2364.66  4955.2 2364.48
  4955.5 2363.98  4959.2 2364.48  4982.6  2364.9  4992.6 2366.13  4996.3 2365.49
  5007.8 2366.43  5035.4 2365.52  5057.4 2366.93  5090.1 2367.22  5095.7 2368.59
    5112 2369.07  5146.9 2372.35  5183.6 2373.75    5200 2372.99  5205.6 2373.76
  5214.8 2373.58  5271.6 2377.25  5282.2 2378.93  5309.9 2379.77    5362 2383.36
#Mann= 8 ,-1 , 0
  4603.7     .07       0  4607.9    .035       0  4646.4     .07       0
  4820.8    .035       0  4860.6     .07       0  4955.2    .035       0
  4959.2     .07       0  4982.6    .035       0
Bank Sta=4955.2,4959.2
XS Rating Curve= 0 ,0
Exp/Cntr=0.3,0.1

Type RM Length L Ch R = 1 ,3216    ,247,247,247
BEGIN DESCRIPTION:
Seale Creek Trib2 4363
END DESCRIPTION:
XS GIS Cut Line= 3
      1353005.94      6828363.66       1353193.4      6828236.09
      1353188.19      6827988.69
#Sta/Elev= 30
  4802.7 2368.74  4826.7 2367.41  4835.6 2367.86  4841.7 2367.19  4892.5 2365.87
  4898.6 2365.35  4907.5 2365.28  4934.6 2363.38  4957.6 2362.66  4970.9 2362.03
  4979.3  2362.1  4985.3 2361.33  5019.3 2360.94  5019.5 2360.44    5023 2360.44
  5023.3 2360.94  5027.4 2361.34  5047.5 2361.68  5067.5 2361.31  5087.6    2362
  5097.6  2363.7  5104.5 2364.24  5117.6 2364.31  5127.6  2365.4  5147.6 2365.09
  5157.6 2366.56  5177.6 2368.01  5191.7 2368.46  5197.6  2369.5  5276.9 2375.94
#Mann= 5 ,-1 , 0
  4802.7    .035       0  4957.6     .07       0  5019.3     .07       0
  5023.3     .07       0  5104.5    .035       0
Bank Sta=5019.3,5023.3
XS Rating Curve= 0 ,0
Exp/Cntr=0.3,0.1

Type RM Length L Ch R = 1 ,2969    ,500,500,500
BEGIN DESCRIPTION:
Seale Creek Trib2 5.0
END DESCRIPTION:
XS GIS Cut Line= 3
        1353305.      6828488.03      1353348.07       6828196.9
        1353255.        6827988.
#Sta/Elev= 30
  4705.7 2367.34    4708 2367.34  4796.7  2363.6  4847.3 2357.75  4874.5 2357.62
  4879.6 2358.96  4887.7 2358.99  4928.1 2357.54  4944.1 2358.48  4949.1 2360.79
  4958.5 2362.44  4968.6 2360.84  4978.7  2357.5  4986.8 2356.72    4987 2356.22
  4990.8 2356.72  4996.9 2360.19  5009.7 2359.44  5019.4 2360.17    5023 2361.24
  5031.6 2361.78  5040.8 2361.37  5069.5  2362.8  5075.4 2364.37  5086.4  2364.4
  5108.3 2366.89  5121.4 2367.09  5162.4 2369.96  5206.8 2373.39  5228.7 2375.88
#Mann= 5 ,-1 , 0
  4705.7    .035       0    4708     .07       0  4986.8     .07       0
  4990.8     .07       0  5019.4    .035       0
Bank Sta=4986.8,4990.8
XS Rating Curve= 0 ,0
Exp/Cntr=0.3,0.1

Type RM Length L Ch R = 1 ,2469    ,271,271,271
BEGIN DESCRIPTION:
Seale Creek Trib2 4.0
END DESCRIPTION:
XS GIS Cut Line= 3
        1353705.        6828338.      1353800.03      6828238.06
        1353555.        6827938.
#Sta/Elev= 30
  4862.1 2356.72  4897.5 2355.78  4911.6    2354  4918.5 2353.73  4925.8 2352.75
  4946.9 2351.85    4961 2350.73  4968.3 2349.54  4989.3 2349.64    5000 2346.51
  5003.3 2347.33  5009.2  2346.5  5009.4    2346  5012.9    2346  5013.2  2346.5
  5017.6 2346.82  5025.6 2349.03    5032 2348.56  5038.8 2350.57  5046.4 2351.55
  5067.2 2353.05  5089.4 2352.64  5095.9 2353.03  5131.1 2353.24  5145.4 2354.02
  5153.3 2353.81    5302 2359.15  5322.8 2360.51  5373.8 2362.39  5387.4  2363.4
#Mann= 3 ,-1 , 0
  4862.1    .035       0  5009.2    .035       0  5013.2    .035       0
Bank Sta=5009.2,5013.2
XS Rating Curve= 0 ,0
Exp/Cntr=0.3,0.1

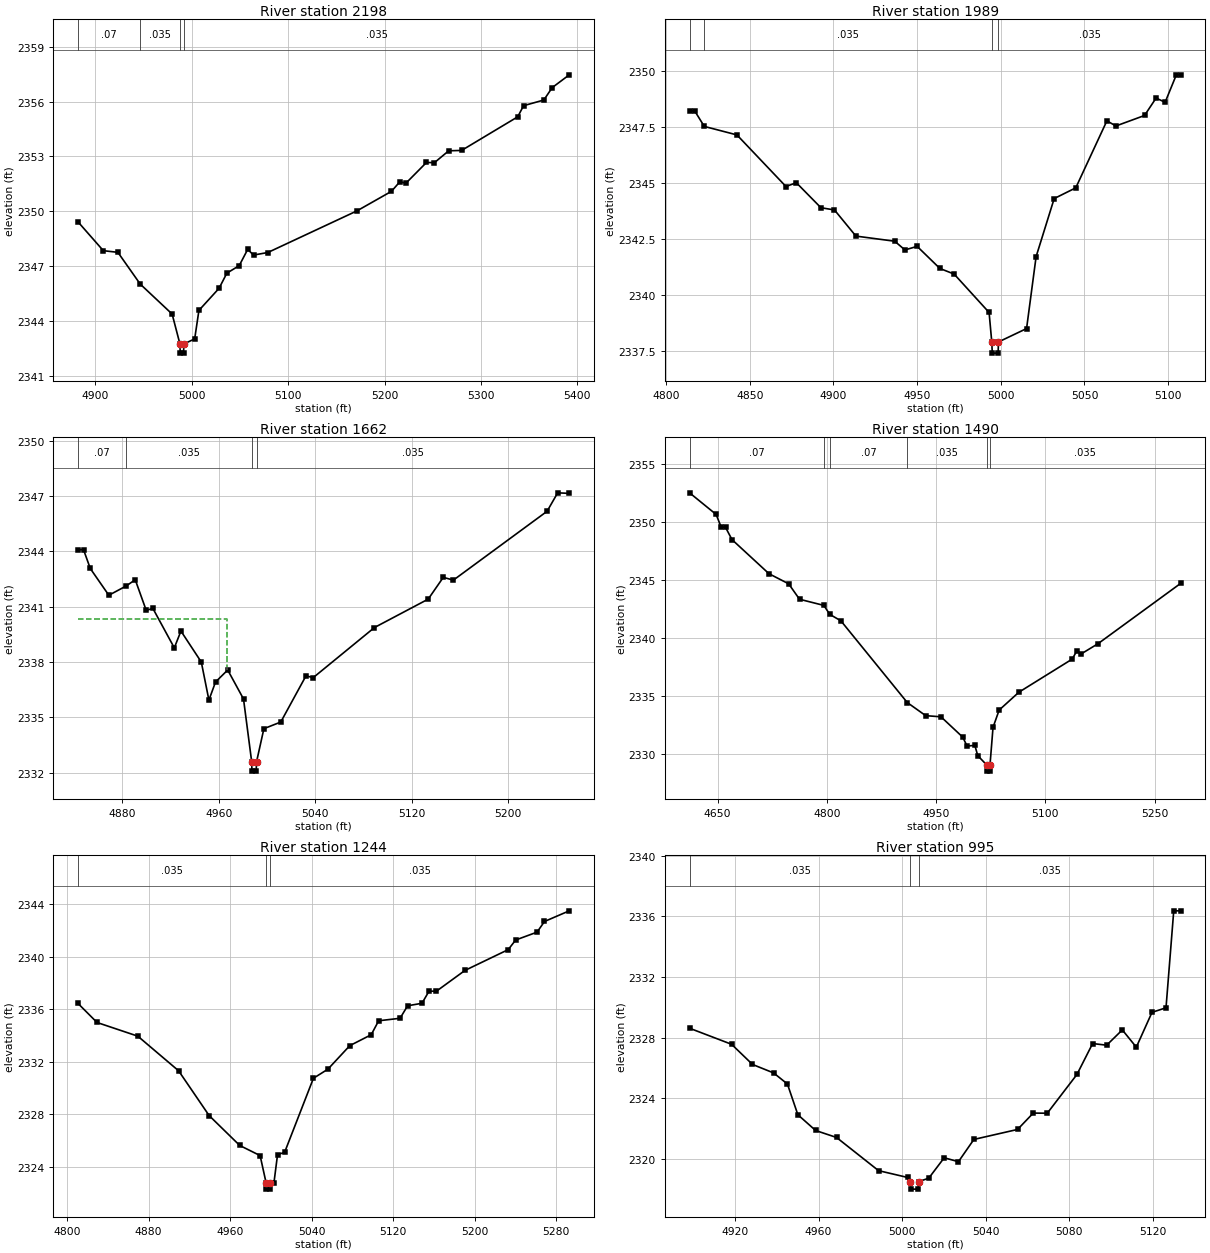
Type RM Length L Ch R = 1 ,2198    ,209,209,209
BEGIN DESCRIPTION:
Seale Creek Trib2 4364
END DESCRIPTION:
XS GIS Cut Line= 3
      1354031.95      6828303.76      1354054.97      6828187.92
      1353831.41      6827866.28
#Sta/Elev= 30
  4881.9 2349.42  4908.2 2347.84  4923.3 2347.75  4946.5 2346.01  4979.6 2344.37
  4987.7 2342.73    4988 2342.23  4991.5 2342.23  4991.7 2342.73    5003 2343.01
  5007.4 2344.57  5028.3 2345.78  5036.4 2346.61  5049.2 2347.02    5058 2347.91
  5064.1  2347.6  5078.9 2347.74  5171.4 2350.02  5207.2 2351.09    5216 2351.62
  5222.1 2351.53  5243.5 2352.67  5251.8 2352.66  5266.6 2353.31    5280 2353.33
  5338.2 2355.17  5344.3 2355.78  5365.3 2356.09    5374 2356.77  5391.7 2357.47
#Mann= 4 ,-1 , 0
  4881.9     .07       0  4946.5    .035       0  4987.7    .035       0
  4991.7    .035       0
Bank Sta=4987.7,4991.7
XS Rating Curve= 0 ,0
Exp/Cntr=0.3,0.1

Type RM Length L Ch R = 1 ,1989    ,327,327,327
BEGIN DESCRIPTION:
Seale Creek Trib2 3.0
END DESCRIPTION:
XS GIS Cut Line= 3
      1354154.97      6828338.04      1354264.28      6828187.55
      1354305.02      6828087.96
#Sta/Elev= 30
    4814 2348.23  4817.1 2348.23  4822.8 2347.54  4842.3 2347.16  4871.6 2344.85
  4877.8 2345.02  4892.5  2343.9  4900.6  2343.8  4913.4 2342.63  4936.6  2342.4
  4942.7 2342.01    4950 2342.17  4963.6 2341.18  4972.1 2340.93    4993 2339.21
  4994.6 2337.89  4994.9 2337.39  4998.4 2337.39  4998.6 2337.89  5015.4 2338.49
  5021.1 2341.71  5031.9 2344.31  5044.8 2344.79  5063.4 2347.79  5068.8 2347.56
  5085.9 2348.03  5092.8 2348.81  5098.2 2348.62  5104.9 2349.85  5107.6 2349.85
#Mann= 4 ,-1 , 0
    4814     .07       0  4822.8    .035       0  4994.6    .035       0
  4998.6    .035       0
Bank Sta=4994.6,4998.6
XS Rating Curve= 0 ,0
Exp/Cntr=0.3,0.1

Type RM Length L Ch R = 1 ,1662    ,172,172,172
BEGIN DESCRIPTION:
Seale Creek Trib2 4361
END DESCRIPTION:
XS GIS Cut Line= 3
      1354495.47      6828431.42      1354559.31       6828288.1
      1354416.68      6828082.04
#Sta/Elev= 30
  4843.1 2344.09  4847.7 2344.09  4853.3 2343.07  4868.7 2341.62    4883 2342.12
  4890.6 2342.46  4899.7  2340.8  4905.2 2340.91    4923 2338.77  4928.5 2339.68
  4945.4    2338  4951.7 2335.94  4957.2 2336.92  4967.3 2337.57  4980.4    2336
  4987.2 2332.59  4987.4 2332.09  4990.9 2332.09  4991.2 2332.59  4997.3 2334.39
  5011.3 2334.75  5032.2 2337.25  5038.3 2337.16    5089 2339.87  5133.6 2341.41
  5146.1 2342.59  5154.5 2342.44  5232.2 2346.17    5241 2347.17  5250.6 2347.14
#Mann= 4 ,-1 , 0
  4843.1     .07       0    4883    .035       0  4987.2    .035       0
  4991.2    .035       0
#XS Ineff= 2 , 0
            4967 2340.33
Permanent Ineff=
       F       F
Bank Sta=4987.2,4991.2
XS Rating Curve= 0 ,0
Exp/Cntr=0.3,0.1

Type RM Length L Ch R = 1 ,1490    ,246,246,246
BEGIN DESCRIPTION:
Seale Creek Trib2 2.0
END DESCRIPTION:
XS GIS Cut Line= 3
      1354504.99      6828588.02      1354724.96      6828267.91
      1354555.01      6828038.01
#Sta/Elev= 30
  4611.6  2352.5    4648 2350.64  4654.9 2349.56    4661 2349.52  4669.8 2348.47
  4720.6 2345.53  4747.6 2344.66  4762.5 2343.33  4795.9  2342.8    4804 2342.03
  4819.3 2341.47  4910.4 2334.43  4935.7  2333.3  4956.7  2333.2  4986.5 2331.45
  4992.5 2330.68  5003.1 2330.74  5007.2 2329.85  5019.9 2329.02  5020.1 2328.52
  5023.6 2328.52  5023.9 2329.02  5028.1 2332.29  5036.5 2333.78  5063.6 2335.32
  5136.7 2338.17  5142.9 2338.85  5149.1 2338.62  5172.2  2339.5  5285.9 2344.71
#Mann= 6 ,-1 , 0
  4611.6     .07       0  4795.9    .035       0    4804     .07       0
  4910.4    .035       0  5019.9    .035       0  5023.9    .035       0
Bank Sta=5019.9,5023.9
XS Rating Curve= 0 ,0
Exp/Cntr=0.3,0.1

Type RM Length L Ch R = 1 ,1244    ,249,249,249
BEGIN DESCRIPTION:
Seale Creek Trib2 4366
END DESCRIPTION:
XS GIS Cut Line= 3
        1354946.      6828376.75      1354944.81      6828187.55
      1354745.49      6827973.07
#Sta/Elev= 30
  4810.8 2336.44  4829.5 2334.99  4869.5 2333.95  4909.5 2331.32  4939.5 2327.91
  4969.5 2325.64  4989.5 2324.87  4995.3 2322.82  4995.5 2322.32    4999 2322.32
  4999.3 2322.82  5003.1 2322.82  5006.6 2324.95  5013.5 2325.11  5041.8 2330.75
    5056 2331.44  5077.5 2333.23  5098.5 2334.06  5105.8 2335.12  5126.8 2335.31
  5134.2 2336.26  5148.3 2336.45  5155.2 2337.37  5162.5 2337.37  5190.5 2338.95
  5232.9 2340.53  5240.2 2341.26  5261.2 2341.86  5268.5 2342.67  5292.8 2343.48
#Mann= 3 ,-1 , 0
  4810.8    .035       0  4995.3    .035       0  4999.3    .035       0
Bank Sta=4995.3,4999.3
XS Rating Curve= 0 ,0
Exp/Cntr=0.3,0.1

Type RM Length L Ch R = 1 ,995     ,496,496,496
BEGIN DESCRIPTION:
Seale Creek Trib2 1.0
END DESCRIPTION:
XS GIS Cut Line= 3
        1355205.      6828287.96       1355194.5       6828186.8
      1355105.01      6828088.01
#Sta/Elev= 30
  4898.3 2328.62  4918.4 2327.56  4928.4 2326.23  4938.5 2325.67  4945.1 2324.94
  4950.1 2322.91  4958.6 2321.87  4968.6 2321.41  4988.7 2319.22  5002.6 2318.77
  5003.9  2318.5  5004.2    2318  5007.7    2318  5007.9  2318.5  5012.7 2318.72
  5020.1 2320.07  5026.9 2319.81  5034.3 2321.28  5055.2 2321.94  5062.7 2323.02
  5069.4 2323.01  5083.6 2325.57  5091.1 2327.61  5097.8  2327.5  5105.3 2328.51
    5112 2327.37  5119.5 2329.67  5126.2 2329.97  5129.9 2336.37  5133.3 2336.37
#Mann= 3 ,-1 , 0
  4898.3    .035       0  5003.9    .035       0  5007.9    .035       0
Bank Sta=5003.9,5007.9
XS Rating Curve= 0 ,0
Exp/Cntr=0.3,0.1

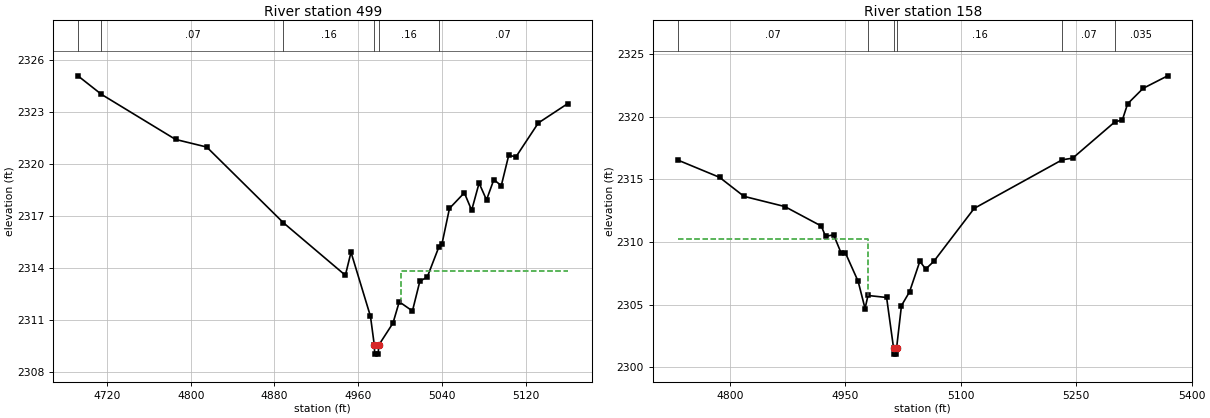
Type RM Length L Ch R = 1 ,499     ,341,341,341
BEGIN DESCRIPTION:
Seale Creek Trib2 2047
END DESCRIPTION:
XS GIS Cut Line= 3
      1355504.99      6828288.01      1355618.13      6828001.76
      1355505.02      6827888.02
#Sta/Elev= 30
  4692.2 2325.07  4714.7    2324  4785.5  2321.4  4815.3 2320.96  4888.6 2316.59
  4947.8 2313.56  4953.2 2314.89  4971.8 2311.19  4975.5 2309.51  4975.8 2309.01
  4979.3 2309.01  4979.5 2309.51  4993.3  2310.8  4999.3 2312.03  5011.9  2311.5
    5019 2313.22  5026.1 2313.46    5037 2315.17  5040.2 2315.39  5047.3 2317.42
  5061.5 2318.32  5068.5 2317.31  5075.6 2318.88  5082.7 2317.91  5089.7 2319.08
  5096.8 2318.73  5103.9 2320.48  5110.9  2320.4  5132.2 2322.35  5160.4 2323.47
#Mann= 6 ,-1 , 0
  4692.2    .035       0  4714.7     .07       0  4888.6     .16       0
  4975.5     .07       0  4979.5     .16       0    5037     .07       0
#XS Ineff= 2 , 0
                         5000.81         2313.81
Permanent Ineff=
       F       F
Bank Sta=4975.5,4979.5
XS Rating Curve= 0 ,0
Exp/Cntr=0.3,0.1

Type RM Length L Ch R = 1 ,158     ,0,0,0
BEGIN DESCRIPTION:
Seale Creek Trib2 4365
END DESCRIPTION:
XS GIS Cut Line= 3
      1355818.39      6828189.25      1355906.84      6827936.48
       1355555.4      6827824.64
#Sta/Elev= 30
  4732.2 2316.54  4786.5 2315.16  4818.3 2313.64  4871.2 2312.83  4918.8 2311.27
  4924.2 2310.45  4934.8 2310.57  4944.6  2309.1  4949.9 2309.15  4966.6 2306.86
  4975.6 2304.69  4979.4 2305.73  5003.6 2305.57  5012.6 2301.55  5012.8 2301.05
  5016.3 2301.05  5016.6 2301.55  5022.9 2304.92  5033.4 2306.02  5046.8 2308.46
  5054.4 2307.84  5064.9 2308.45  5117.4 2312.68  5231.8 2316.56  5245.4 2316.69
  5300.3 2319.59  5309.9 2319.73  5316.8 2321.03  5336.9 2322.26  5368.8 2323.26
#Mann= 6 ,-1 , 0
  4732.2     .07       0  4979.4     .16       0  5012.6     .07       0
  5016.6     .16       0  5231.8     .07       0  5300.3    .035       0
#XS Ineff= 2 , 0
            4980 2310.24
Permanent Ineff=
       F       F
Bank Sta=5012.6,5016.6
XS Rating Curve= 0 ,0
Exp/Cntr=0.3,0.1

Chan Stop Cuts=-1
Use User Specified Reach Order=0
Composite Channel Slope=5