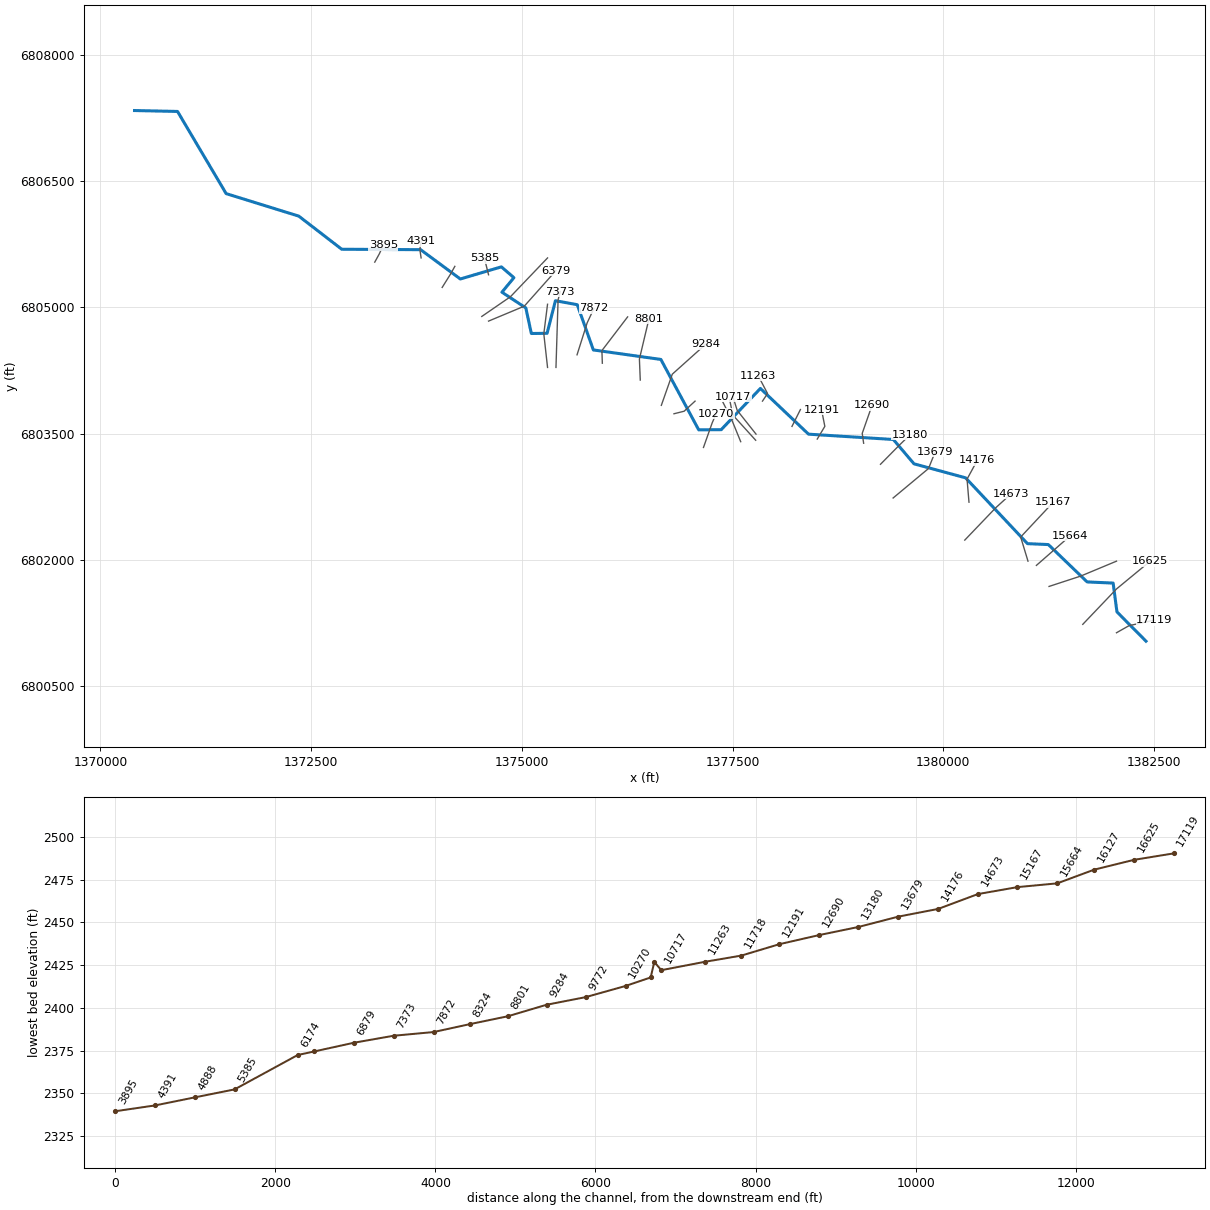
--- Spring Creek.prj (project) ---

Proj Title=Spring Creek Base Level Engineering
Current Plan=p01
Default Exp/Contr=0.3,0.1
English Units
Geom File=g01
Flow File=f01
Plan File=p01
Y Axis Title=Elevation
X Axis Title(PF)=Main Channel Distance
X Axis Title(XS)=Station
BEGIN DESCRIPTION:
Spring Creek
END DESCRIPTION:
DSS Export Rating Curves= 0
DSS Export Rating Curve Sorted= 0
DSS Export Volume Flow Curves= 0
DXF OffsetX= 0
DXF OffsetY= 0
DXF ScaleX= 1
DXF ScaleY= 10

--- Spring Creek.p01 (plan) ---

Plan Title=Multiple Run
Short Identifier=Multiple
Geom File=g01
Flow File=f01
Subcritical Flow
K Sum by GR= 0
Std Step Tol= 0.01
Critical Tol= 0.01
Num of Std Step Trials= 20
Max Error Tol= 0.3
Flow Tol Ratio= 0.001
Split Flow NTrial= 30
Split Flow Tol= 0.02
Split Flow Ratio= 0.02
Log Output Level= 0
Friction Slope Method= 1
Unsteady Friction Slope Method= 2
Unsteady Bridges Friction Slope Method= 1
Parabolic Critical Depth
Global Vel Dist=  1 , 1 , 1
Global Log Level= 0
CheckData=True
Encroach Param= -1, 0, 0, 0
BEGIN DESCRIPTION:
Multiple Run
END DESCRIPTION:

--- Spring Creek.f01 (steady flow) ---

Flow Title=Multiple
Number of Profiles=7
Profile Names=10-year,25-year,50-year,1pct_min,100-year,1pct_plu,500-year
River Rch & RM= Spring Creek,Reach-1,17119
     512     753     963     612    1221    2436    1989
River Rch & RM= Spring Creek,Reach-1,12191
     673    1003    1293     828    1652    3296    2732
River Rch & RM= Spring Creek,Reach-1,4391
     720    1081    1401     901    1798    3587    3003
Boundary for River Rch & Prof#=Spring Creek,Reach-1,1
Up Type=0
Dn Type=3
Dn Slope=0.005
Boundary for River Rch & Prof#=Spring Creek,Reach-1,2
Up Type=0
Dn Type=3
Dn Slope=0.005
Boundary for River Rch & Prof#=Spring Creek,Reach-1,3
Up Type=0
Dn Type=3
Dn Slope=0.005
Boundary for River Rch & Prof#=Spring Creek,Reach-1,4
Up Type=0
Dn Type=3
Dn Slope=0.005
Boundary for River Rch & Prof#=Spring Creek,Reach-1,5
Up Type=0
Dn Type=3
Dn Slope=0.005
Boundary for River Rch & Prof#=Spring Creek,Reach-1,6
Up Type=0
Dn Type=3
Dn Slope=0.005
Boundary for River Rch & Prof#=Spring Creek,Reach-1,7
Up Type=0
Dn Type=3
Dn Slope=0.005

--- Spring Creek.g01 (geometry) ---

Geom Title=Existing Conditions

River Reach=Spring Creek,Reach-1
Reach XY= 30
      1382405.00      6801038.00      1382060.46      6801385.55
      1382015.18      6801727.68      1381706.45      6801741.53
      1381246.36      6802185.00      1380998.83      6802195.86
      1380264.68      6802977.24      1379652.64      6803143.75
      1379407.43      6803432.48      1378401.34      6803495.67
      1377830.11      6804038.32      1377365.00      6803548.96
      1377098.27      6803547.13      1376649.56      6804382.82
      1375848.48      6804495.67      1375657.68      6805032.58
      1375398.50      6805080.38      1375299.59      6804693.17
      1375112.92      6804690.91      1375047.26      6804994.45
      1374763.77      6805181.20      1374905.94      6805353.41
      1374757.28      6805482.18      1374270.39      6805338.07
      1373799.14      6805685.94      1372863.34      6805691.16
      1372353.50      6806084.39      1371491.79      6806351.62
      1370915.02      6807327.05      1370405.00      6807338.00

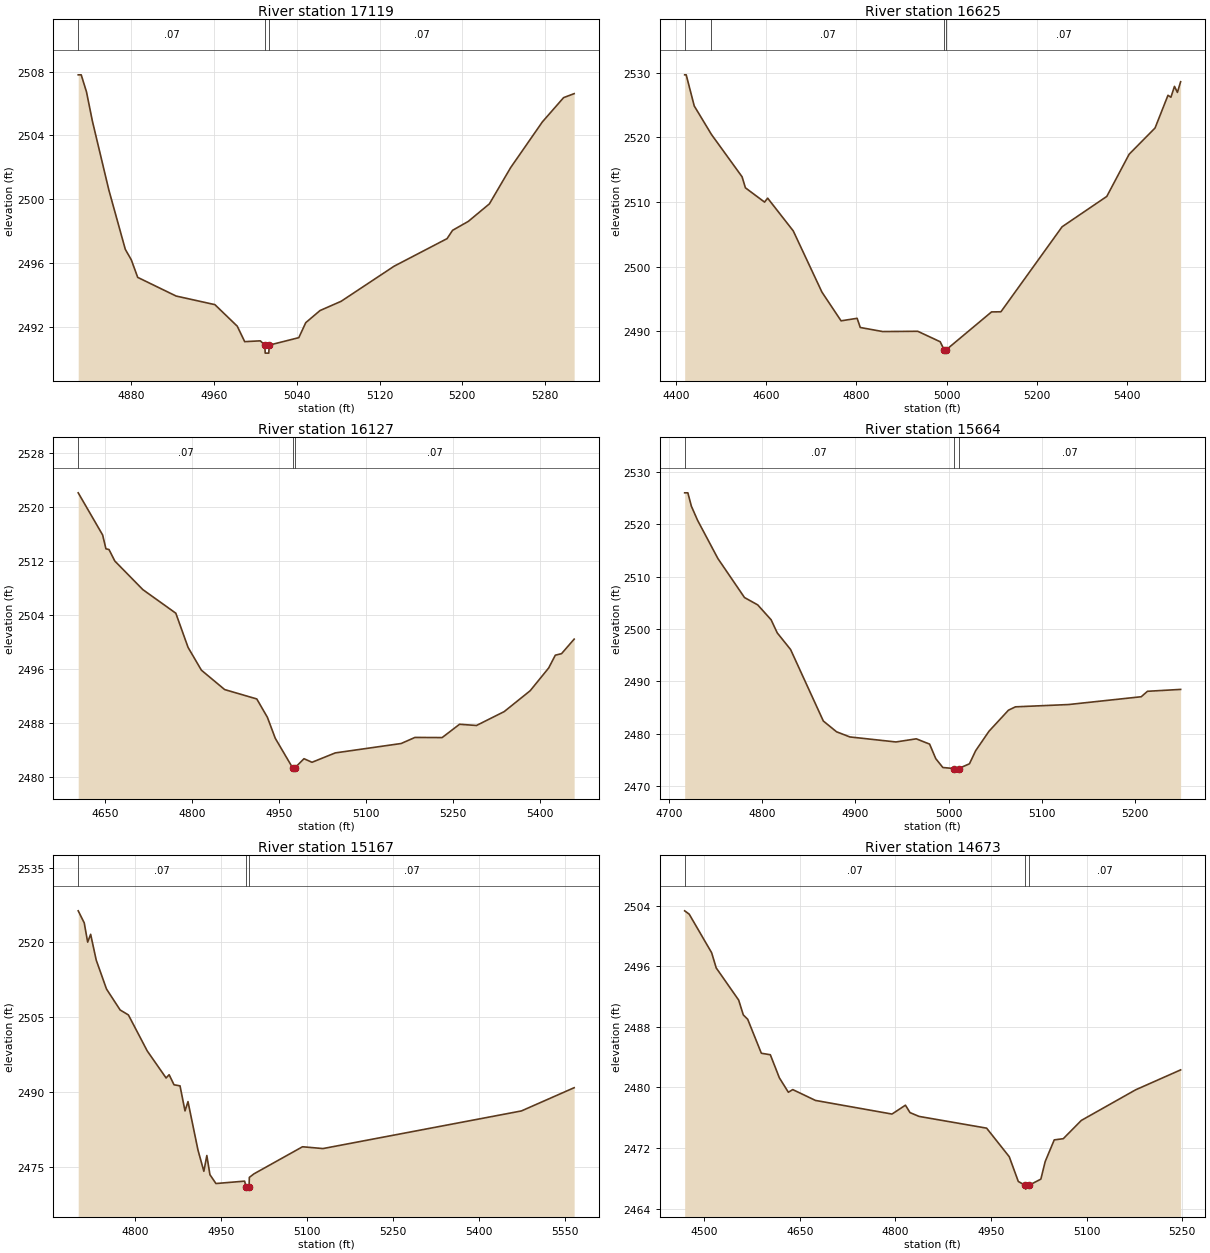
Type RM Length L Ch R = 1,17119,494,494,494
BEGIN DESCRIPTION:
Spring Creek 34.0
END DESCRIPTION:
XS GIS Cut Line= 3
      1382054.98      6801137.99      1382203.98      6801222.29
      1382504.99      6801288.00
#Sta/Elev= 30
  4828.8 2507.80  4831.7 2507.80  4836.8 2506.73  4842.5 2504.90  4858.4 2500.58
  4874.3 2496.86  4880.1 2496.20  4886.3 2495.10  4923.4 2493.93  4960.9 2493.39
  4982.5 2492.04  4989.7 2491.07  5004.8 2491.12  5009.2 2490.85  5009.5 2490.35
  5013.0 2490.35  5013.3 2490.85  5042.0 2491.32  5048.7 2492.26  5062.5 2493.02
  5082.9 2493.60  5134.1 2495.80  5185.3 2497.53  5190.6 2498.05  5205.8 2498.61
  5226.2 2499.71  5246.7 2501.98  5277.4 2504.85  5297.9 2506.37  5308.1 2506.62
#Mann=3,-1,0
  4828.8    0.07       0  5009.2    0.07       0  5013.3    0.07       0
Bank Sta=5009.2,5013.3
Exp/Cntr=0.3,0.1

Type RM Length L Ch R = 1,16625,498,498,498
BEGIN DESCRIPTION:
Spring Creek 33.0
END DESCRIPTION:
XS GIS Cut Line= 3
      1381655.00      6801238.00      1382055.46      6801658.26
      1382454.97      6801987.98
#Sta/Elev= 30
  4419.5 2529.68  4422.9 2529.68  4440.7 2524.86  4478.9 2520.44  4546.7 2513.89
  4554.0 2512.19  4596.4 2509.98  4603.3 2510.59  4660.0 2505.52  4723.5 2496.05
  4765.9 2491.60  4801.5 2491.99  4808.4 2490.57  4858.1 2489.94  4935.8 2489.98
  4985.5 2488.36  4994.3 2487.10  4994.6 2486.60  4998.5 2487.10  5099.2 2492.98
  5120.0 2493.00  5255.5 2506.16  5354.5 2510.86  5404.0 2517.39  5461.4 2521.45
  5490.0 2526.51  5496.5 2526.21  5504.4 2527.89  5510.9 2526.96  5518.0 2528.61
#Mann=4,-1,0
  4419.5    0.16       0  4478.9    0.07       0  4994.3    0.07       0
  4998.5    0.07       0
Bank Sta=4994.3,4998.5
Exp/Cntr=0.3,0.1

Type RM Length L Ch R = 1,16127,463,463,463
BEGIN DESCRIPTION:
Spring Creek 32.0
END DESCRIPTION:
XS GIS Cut Line= 3
      1381255.00      6801688.00      1381631.27      6801811.11
      1382055.03      6801988.01
#Sta/Elev= 30
  4604.1 2522.08  4646.2 2515.84  4651.9 2513.79  4657.2 2513.68  4667.2 2511.98
  4715.6 2507.74  4772.4 2504.25  4793.5 2499.19  4816.5 2495.81  4856.6 2492.94
  4912.0 2491.55  4930.3 2488.83  4943.9 2485.72  4973.7 2481.36  4973.9 2480.86
  4977.9 2481.36  4993.4 2482.70  5007.2 2482.17  5047.4 2483.56  5160.9 2484.95
  5184.7 2485.85  5231.6 2485.83  5261.6 2487.80  5290.8 2487.62  5338.5 2489.67
  5383.3 2492.76  5415.3 2496.14  5426.7 2498.03  5437.5 2498.26  5459.2 2500.41
#Mann=3,-1,0
  4604.1    0.07       0  4973.7    0.07       0  4977.9    0.07       0
Bank Sta=4973.7,4977.9
Exp/Cntr=0.3,0.1

Type RM Length L Ch R = 1,15664,497,497,497
BEGIN DESCRIPTION:
Spring Creek 31.0
END DESCRIPTION:
XS GIS Cut Line= 3
      1381104.97      6801937.97      1381317.99      6802124.29
      1381504.96      6802287.97
#Sta/Elev= 30
  4717.0 2525.99  4720.4 2525.99  4724.2 2523.43  4730.8 2520.75  4752.6 2513.44
  4781.1 2505.99  4795.3 2504.58  4809.6 2501.75  4816.2 2499.24  4830.5 2496.06
  4865.6 2482.40  4879.8 2480.34  4894.1 2479.36  4943.4 2478.40  4965.2 2479.00
  4979.5 2477.99  4986.1 2475.21  4993.7 2473.52  5005.4 2473.33  5005.8 2472.83
  5010.6 2473.33  5022.2 2474.23  5028.8 2476.72  5043.1 2480.44  5064.0 2484.47
  5071.5 2485.11  5128.5 2485.55  5206.3 2487.04  5213.0 2488.08  5248.5 2488.44
#Mann=3,-1,0
  4717.0    0.07       0  5005.4    0.07       0  5010.6    0.07       0
Bank Sta=5005.4,5010.6
Exp/Cntr=0.3,0.1

Type RM Length L Ch R = 1,15167,494,494,494
BEGIN DESCRIPTION:
Spring Creek 30.0
END DESCRIPTION:
XS GIS Cut Line= 3
      1381005.01      6801987.96      1380918.22      6802274.60
      1381304.98      6802687.98
#Sta/Elev= 30
  4700.5 2526.34  4711.0 2523.93  4717.0 2520.07  4722.2 2521.64  4731.9 2516.49
  4749.9 2510.68  4773.7 2506.49  4788.1 2505.50  4821.0 2498.29  4853.9 2492.88
  4859.2 2493.53  4867.7 2491.52  4878.2 2491.30  4886.9 2486.29  4892.1 2488.15
  4909.5 2478.47  4919.8 2474.20  4925.0 2477.36  4930.4 2473.52  4940.9 2471.75
  4990.9 2472.23  4993.5 2471.13  4993.9 2470.63  4998.7 2471.13  4999.2 2472.98
  5007.1 2473.68  5092.0 2479.11  5127.7 2478.75  5474.0 2486.28  5566.1 2490.93
#Mann=3,-1,0
  4700.5    0.07       0  4993.5    0.07       0  4998.7    0.07       0
Bank Sta=4993.5,4998.7
Exp/Cntr=0.3,0.1

Type RM Length L Ch R = 1,14673,497,497,497
BEGIN DESCRIPTION:
Spring Creek 29.0
END DESCRIPTION:
XS GIS Cut Line= 3
      1380255.02      6802238.02      1380622.04      6802621.48
      1380805.01      6802788.01
#Sta/Elev= 30
  4469.2 2503.30  4476.3 2502.86  4511.5 2497.77  4518.7 2495.76  4553.9 2491.52
  4561.2 2489.56  4568.1 2488.98  4589.5 2484.50  4603.6 2484.30  4617.8 2481.25
  4631.9 2479.35  4638.8 2479.70  4674.4 2478.27  4794.5 2476.47  4815.6 2477.64
  4822.8 2476.66  4837.0 2476.16  4943.0 2474.61  4978.5 2470.84  4992.7 2467.57
  5003.7 2467.06  5004.2 2466.56  5009.3 2467.06  5028.1 2467.88  5034.9 2470.20
  5049.1 2473.06  5063.3 2473.22  5091.6 2475.63  5176.8 2479.67  5247.4 2482.30
#Mann=3,-1,0
  4469.2    0.07       0  5003.7    0.07       0  5009.3    0.07       0
Bank Sta=5003.7,5009.3
Exp/Cntr=0.3,0.1

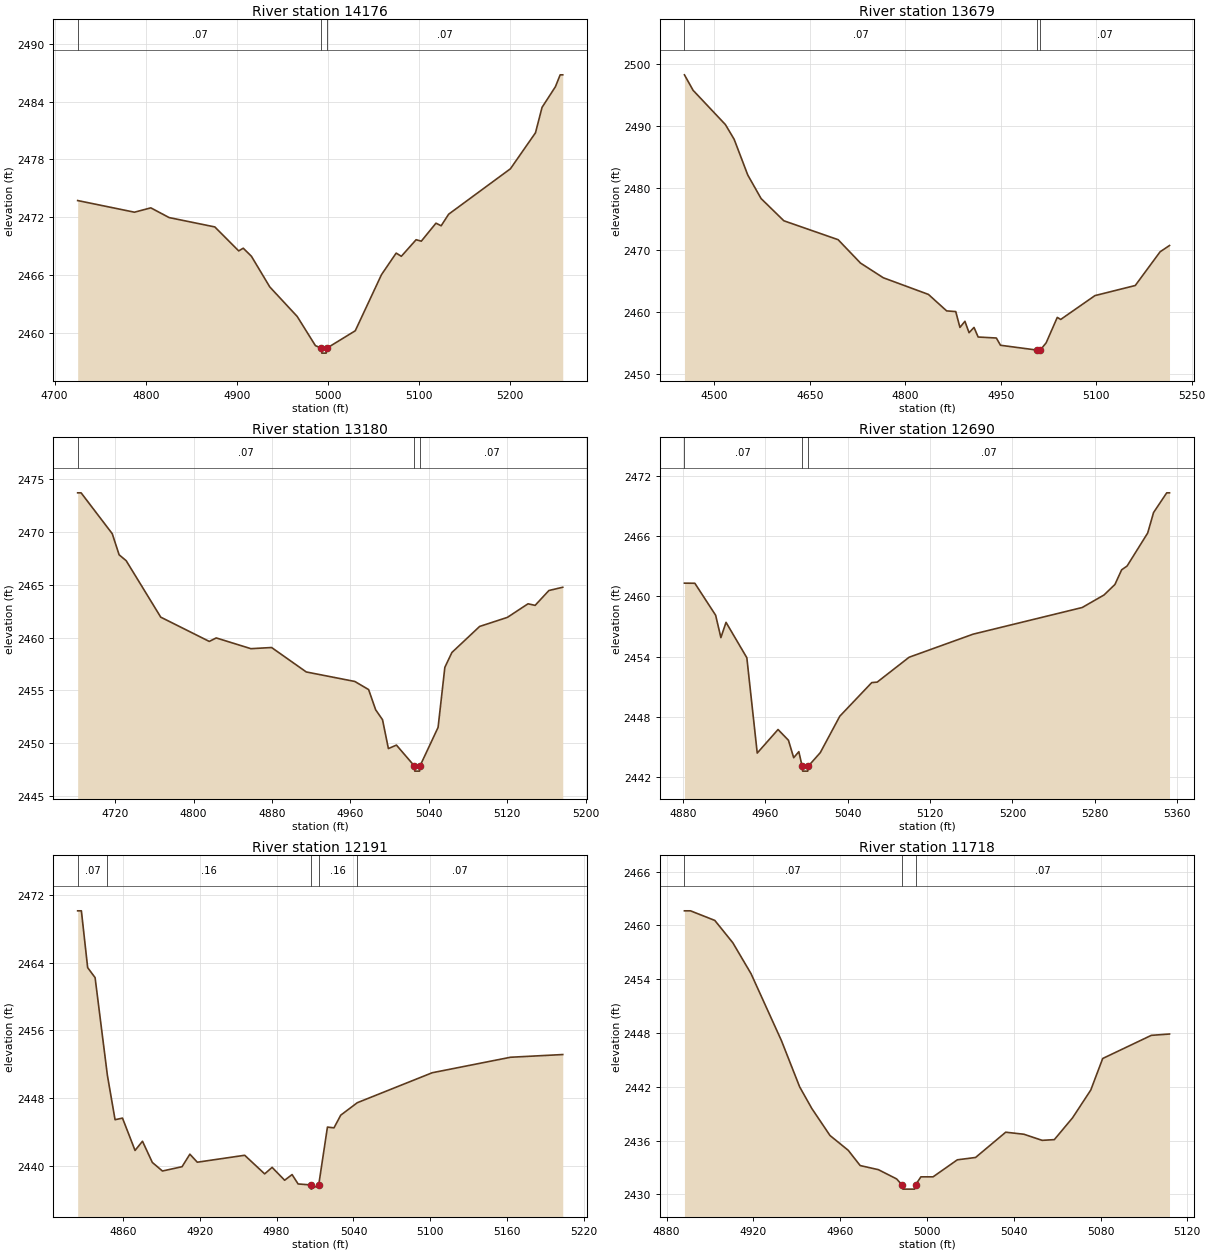
Type RM Length L Ch R = 1,14176,497,497,497
BEGIN DESCRIPTION:
Spring Creek 28.0
END DESCRIPTION:
XS GIS Cut Line= 3
      1380305.00      6802687.99      1380281.82      6802961.71
      1380404.98      6803187.96
#Sta/Elev= 30
  4725.3 2473.72  4787.6 2472.51  4805.6 2472.96  4825.7 2471.95  4875.8 2470.98
  4902.0 2468.49  4907.0 2468.77  4916.0 2467.93  4936.1 2464.75  4966.2 2461.68
  4986.2 2458.65  4992.8 2458.37  4993.2 2457.87  4998.0 2457.87  4998.5 2458.37
  5029.9 2460.19  5058.7 2466.02  5074.8 2468.26  5080.5 2467.93  5096.7 2469.65
  5102.4 2469.50  5118.5 2471.37  5124.2 2471.10  5132.4 2472.30  5200.2 2477.02
  5227.7 2480.76  5234.9 2483.40  5249.6 2485.55  5254.8 2486.78  5257.6 2486.78
#Mann=3,-1,0
  4725.3    0.07       0  4992.8    0.07       0  4998.5    0.07       0
Bank Sta=4992.8,4998.5
Exp/Cntr=0.3,0.1

Type RM Length L Ch R = 1,13679,499,499,499
BEGIN DESCRIPTION:
Spring Creek 27.0
END DESCRIPTION:
XS GIS Cut Line= 3
      1379405.04      6802738.03      1379825.10      6803088.24
      1379904.98      6803287.96
#Sta/Elev= 30
  4453.1 2498.31  4466.7 2495.81  4517.5 2490.27  4531.2 2487.90  4552.6 2482.13
  4573.5 2478.33  4609.3 2474.74  4694.5 2471.69  4729.7 2467.91  4765.5 2465.54
  4836.4 2462.85  4865.0 2460.19  4879.3 2460.08  4885.9 2457.52  4893.7 2458.51
  4900.2 2456.67  4908.0 2457.52  4914.5 2455.97  4943.1 2455.81  4949.6 2454.64
  5006.3 2453.87  5006.8 2453.37  5012.1 2453.87  5021.3 2455.03  5038.8 2459.14
  5044.2 2458.81  5098.0 2462.66  5161.3 2464.29  5200.3 2469.73  5215.1 2470.75
#Mann=3,-1,0
  4453.1    0.07       0  5006.3    0.07       0  5012.1    0.07       0
Bank Sta=5006.3,5012.1
Exp/Cntr=0.3,0.1

Type RM Length L Ch R = 1,13180,490,490,490
BEGIN DESCRIPTION:
Spring Creek 26.0
END DESCRIPTION:
XS GIS Cut Line= 3
      1379255.02      6803138.02      1379478.42      6803364.76
      1379605.02      6803488.02
#Sta/Elev= 30
  4681.7 2473.73  4685.2 2473.73  4717.0 2469.85  4724.0 2467.85  4731.2 2467.29
  4766.5 2461.93  4816.0 2459.63  4823.1 2459.96  4858.5 2458.94  4879.6 2459.05
  4915.0 2456.73  4964.5 2455.83  4978.6 2455.06  4985.8 2453.14  4992.8 2452.20
  4998.8 2449.46  5007.0 2449.79  5025.2 2447.82  5025.7 2447.32  5030.6 2447.32
  5031.1 2447.82  5049.5 2451.47  5056.4 2457.17  5063.6 2458.58  5091.9 2461.05
  5120.2 2461.91  5141.3 2463.20  5148.5 2463.05  5162.6 2464.46  5176.7 2464.77
#Mann=3,-1,0
  4681.7    0.07       0  5025.2    0.07       0  5031.1    0.07       0
Bank Sta=5025.2,5031.1
Exp/Cntr=0.3,0.1

Type RM Length L Ch R = 1,12690,499,499,499
BEGIN DESCRIPTION:
Spring Creek 25.0
END DESCRIPTION:
XS GIS Cut Line= 3
      1379055.00      6803388.01      1379038.25      6803505.32
      1379155.01      6803838.02
#Sta/Elev= 30
  4881.5 2461.33  4891.6 2461.32  4911.8 2458.13  4916.9 2455.90  4921.9 2457.42
  4942.1 2453.89  4952.2 2444.38  4972.4 2446.73  4982.5 2445.66  4987.6 2443.92
  4992.6 2444.52  4995.8 2443.08  4996.3 2442.58  5001.3 2442.58  5001.8 2443.08
  5013.4 2444.42  5032.4 2448.06  5063.4 2451.41  5068.7 2451.46  5099.7 2453.94
  5161.8 2456.24  5267.8 2458.90  5289.0 2460.15  5299.6 2461.20  5306.1 2462.66
  5311.4 2463.04  5331.4 2466.33  5337.1 2468.37  5349.9 2470.34  5352.6 2470.34
#Mann=3,-1,0
  4881.5    0.07       0  4995.8    0.07       0  5001.8    0.07       0
Bank Sta=4995.8,5001.8
Exp/Cntr=0.3,0.1

Type RM Length L Ch R = 1,12191,473,473,473
BEGIN DESCRIPTION:
Spring Creek 24.0
END DESCRIPTION:
XS GIS Cut Line= 3
      1378504.99      6803437.98      1378594.83      6803588.50
      1378555.01      6803787.97
#Sta/Elev= 30
  4824.7 2470.11  4827.6 2470.11  4832.5 2463.40  4838.3 2462.22  4847.9 2450.68
  4853.9 2445.43  4859.7 2445.62  4869.5 2441.80  4875.3 2442.89  4883.0 2440.38
  4890.9 2439.37  4906.2 2439.88  4912.3 2441.36  4918.1 2440.41  4955.1 2441.23
  4970.7 2439.03  4976.5 2439.80  4986.3 2438.28  4992.1 2438.95  4996.8 2437.84
  5006.5 2437.73  5007.0 2437.23  5012.9 2437.73  5019.7 2444.56  5024.8 2444.47
  5030.1 2445.97  5043.0 2447.44  5101.5 2450.98  5162.6 2452.81  5203.4 2453.13
#Mann=5,-1,0
  4824.7    0.07       0  4847.9    0.16       0  5006.5    0.07       0
  5012.9    0.16       0  5043.0    0.07       0
Bank Sta=5006.5,5012.9
Exp/Cntr=0.3,0.1

Type RM Length L Ch R = 1,11718,455,455,455
BEGIN DESCRIPTION:
Spring Creek 23.0
END DESCRIPTION:
XS GIS Cut Line= 3
      1378205.01      6803588.01      1378255.01      6803688.00
      1378305.00      6803788.01
#Sta/Elev= 30
  4888.2 2461.62  4891.0 2461.62  4902.2 2460.55  4910.5 2458.06  4918.9 2454.61
  4932.9 2447.15  4941.3 2441.99  4946.9 2439.58  4955.3 2436.56  4963.7 2434.91
  4969.2 2433.21  4977.6 2432.75  4986.0 2431.72  4988.4 2431.08  4988.9 2430.58
  4994.3 2430.58  4994.8 2431.08  4997.2 2431.95  5002.8 2431.95  5014.0 2433.85
  5022.4 2434.11  5036.3 2436.93  5044.7 2436.70  5053.1 2436.02  5058.7 2436.10
  5067.1 2438.53  5075.5 2441.63  5081.0 2445.15  5103.4 2447.73  5111.8 2447.88
#Mann=3,-1,0
  4888.2    0.07       0  4988.4    0.07       0  4994.8    0.07       0
Bank Sta=4988.4,4994.8
Exp/Cntr=0.3,0.1

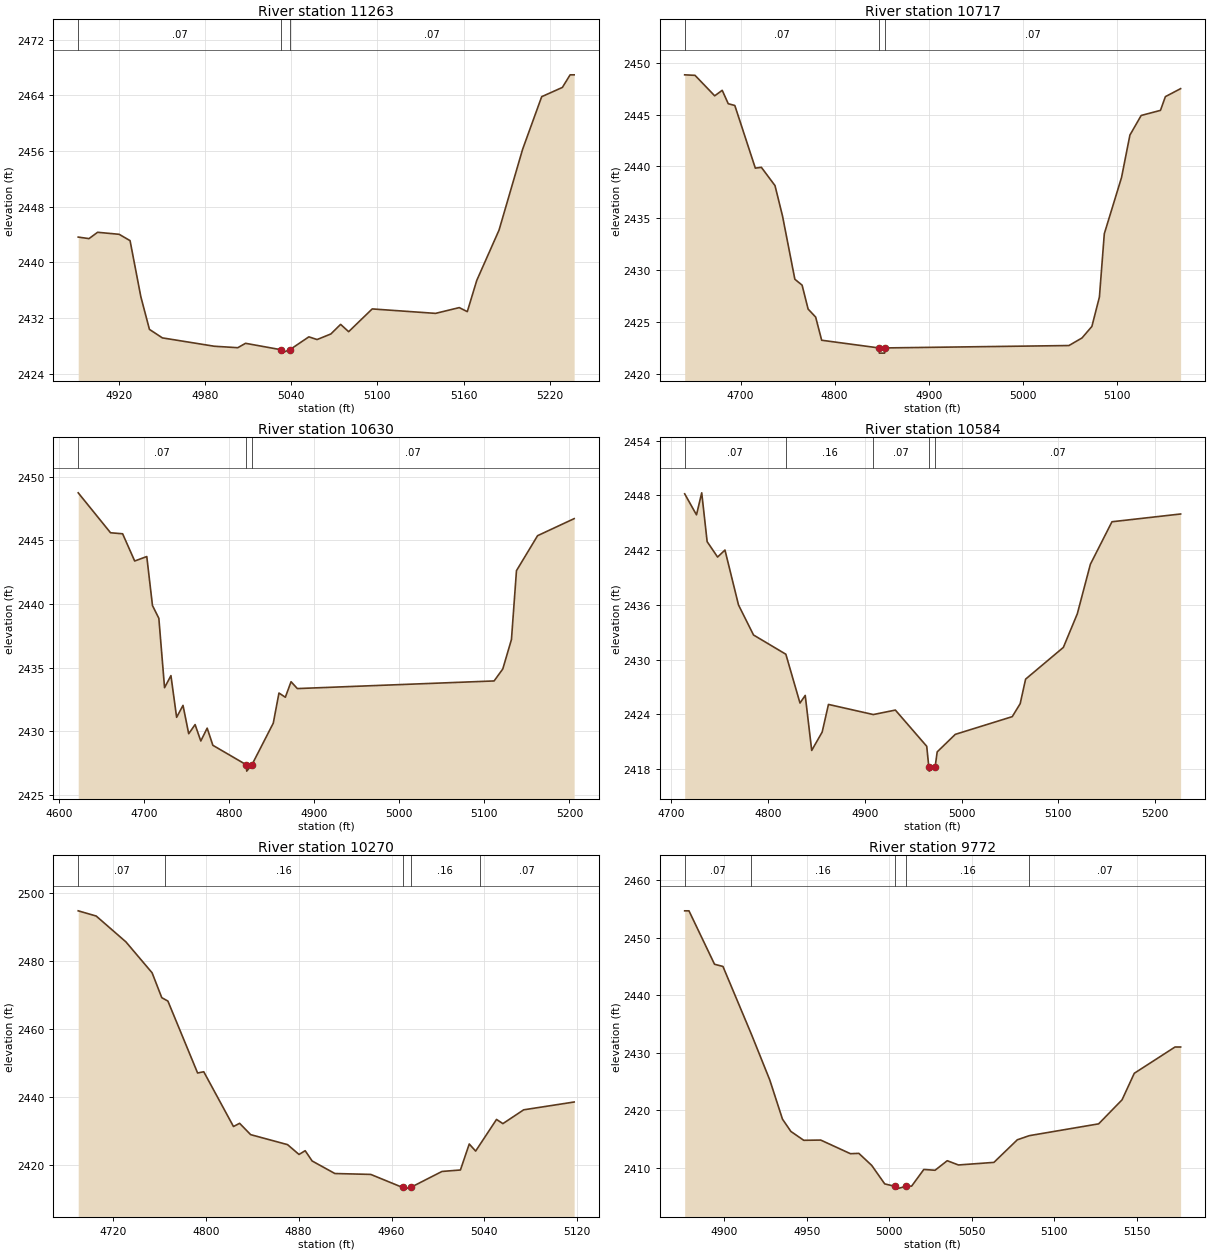
Type RM Length L Ch R = 1,11263,546,546,546
BEGIN DESCRIPTION:
Spring Creek 22.0
END DESCRIPTION:
XS GIS Cut Line= 3
      1377855.00      6803888.00      1377915.05      6803978.12
      1377804.99      6804188.02
#Sta/Elev= 30
  4891.7 2443.62  4899.2 2443.40  4905.2 2444.31  4920.2 2444.02  4927.8 2443.11
  4935.3 2435.06  4941.3 2430.36  4950.3 2429.14  4986.4 2427.94  5002.8 2427.73
  5008.2 2428.36  5032.6 2427.45  5033.1 2426.95  5039.1 2427.45  5052.3 2429.29
  5058.0 2428.90  5067.6 2429.70  5074.4 2431.08  5080.0 2430.03  5096.4 2433.30
  5140.5 2432.66  5157.0 2433.49  5162.6 2432.91  5169.2 2437.40  5184.7 2444.62
  5201.1 2456.22  5214.4 2463.79  5228.8 2465.12  5234.2 2466.93  5237.0 2466.93
#Mann=3,-1,0
  4891.7    0.07       0  5032.6    0.07       0  5039.1    0.07       0
Bank Sta=5032.6,5039.1
Exp/Cntr=0.3,0.1

Type RM Length L Ch R = 1,10717,87,87,87
BEGIN DESCRIPTION:
Spring Creek 21.0
END DESCRIPTION:
XS GIS Cut Line= 3
      1377778.37      6803496.25      1377555.16      6803777.93
      1377505.01      6803937.96
#Sta/Elev= 30
  4640.6 2448.82  4651.6 2448.77  4672.5 2446.80  4680.5 2447.33  4686.9 2446.04
  4693.9 2445.87  4715.7 2439.84  4722.1 2439.92  4736.6 2438.16  4744.6 2435.23
  4757.7 2429.15  4765.4 2428.58  4771.8 2426.28  4779.8 2425.51  4786.2 2423.28
  4847.0 2422.54  4847.5 2422.04  4853.1 2422.04  4853.6 2422.54  5049.0 2422.77
  5062.9 2423.50  5073.4 2424.61  5081.4 2427.44  5086.6 2433.53  5104.9 2438.94
  5113.8 2443.02  5125.8 2444.91  5146.3 2445.40  5151.5 2446.72  5167.7 2447.49
#Mann=3,-1,0
  4640.6    0.07       0  4847.0    0.07       0  4853.6    0.07       0
Bank Sta=4847,4853.6
Exp/Cntr=0.3,0.1

Type RM Length L Ch R = 1,10630,46,46,46
BEGIN DESCRIPTION:
Spring Creek 4141
END DESCRIPTION:
XS GIS Cut Line= 4
      1377774.34      6803423.53      1377520.72      6803703.15
      1377497.45      6803751.64      1377466.20      6803900.10
#Sta/Elev= 30
  4622.5 2448.74  4660.5 2445.60  4674.7 2445.52  4688.9 2443.38  4703.1 2443.73
  4709.8 2439.88  4717.3 2438.87  4724.0 2433.42  4731.5 2434.37  4738.2 2431.09
  4745.7 2432.03  4752.4 2429.80  4759.9 2430.52  4766.6 2429.23  4774.1 2430.24
  4780.8 2428.89  4820.1 2427.36  4820.6 2426.86  4826.7 2427.36  4851.8 2430.63
  4858.5 2433.00  4866.0 2432.67  4872.7 2433.89  4880.1 2433.35  5111.4 2433.95
  5121.6 2434.89  5131.8 2437.21  5137.7 2442.62  5162.5 2445.37  5205.5 2446.71
#Mann=3,-1,0
  4622.5    0.07       0  4820.1    0.07       0  4826.7    0.07       0
Bank Sta=4820.1,4826.7
Exp/Cntr=0.3,0.1

Type RM Length L Ch R = 1,10584,314,314,314
BEGIN DESCRIPTION:
Spring Creek 4158
END DESCRIPTION:
XS GIS Cut Line= 3
      1377596.59      6803406.53      1377488.43      6803671.29
      1377386.53      6803873.24
#Sta/Elev= 30
  4714.0 2448.17  4726.2 2445.87  4731.6 2448.28  4737.2 2442.93  4748.0 2441.24
  4755.6 2442.01  4769.6 2435.99  4785.1 2432.70  4818.5 2430.59  4833.1 2425.24
  4838.5 2426.08  4845.2 2420.05  4856.0 2422.06  4862.5 2425.09  4908.8 2423.98
  4931.6 2424.47  4964.0 2420.50  4966.1 2418.28  4966.6 2417.78  4972.7 2418.28
  4974.8 2419.89  4993.5 2421.81  5052.3 2423.75  5060.5 2425.17  5066.1 2427.86
  5105.1 2431.34  5119.5 2435.02  5133.0 2440.45  5155.3 2445.11  5226.2 2445.96
#Mann=5,-1,0
  4714.0    0.07       0  4818.5    0.16       0  4908.8    0.07       0
  4966.1    0.07       0  4972.7    0.07       0
Bank Sta=4966.1,4972.7
Exp/Cntr=0.3,0.1

Type RM Length L Ch R = 1,10270,498,498,498
BEGIN DESCRIPTION:
Spring Creek 20.0
END DESCRIPTION:
XS GIS Cut Line= 3
      1377154.99      6803337.96      1377258.41      6803630.20
      1377304.98      6803737.96
#Sta/Elev= 30
  4690.0 2494.67  4705.5 2493.14  4731.1 2485.54  4753.7 2476.43  4762.0 2469.13
  4764.6 2468.63  4767.3 2468.12  4792.9 2446.96  4798.2 2447.33  4823.8 2431.22
  4829.1 2432.16  4838.6 2428.83  4870.4 2425.89  4880.3 2423.00  4885.6 2424.10
  4891.6 2421.08  4911.2 2417.39  4942.1 2417.13  4969.5 2413.30  4970.0 2412.80
  4976.5 2413.30  5003.5 2418.00  5019.4 2418.43  5027.0 2426.08  5032.5 2423.99
  5036.3 2425.96  5050.5 2433.30  5056.0 2432.07  5073.9 2436.13  5117.4 2438.43
#Mann=5,-1,0
  4690.0    0.07       0  4764.6    0.16       0  4969.5    0.07       0
  4976.5    0.16       0  5036.3    0.07       0
Bank Sta=4969.5,4976.5
Exp/Cntr=0.3,0.1

Type RM Length L Ch R = 1,9772,488,488,488
BEGIN DESCRIPTION:
Spring Creek 19.0
END DESCRIPTION:
XS GIS Cut Line= 3
      1376804.97      6803737.99      1376925.26      6803768.10
      1377055.03      6803888.03
#Sta/Elev= 30
  4876.0 2454.66  4878.6 2454.66  4894.1 2445.37  4899.2 2444.99  4916.5 2433.17
  4927.6 2425.25  4935.3 2418.44  4940.4 2416.30  4948.2 2414.76  4958.5 2414.80
  4976.5 2412.43  4981.6 2412.49  4989.4 2410.40  4997.3 2407.18  5003.3 2406.77
  5003.8 2406.27  5010.4 2406.77  5013.6 2406.79  5021.0 2409.69  5027.8 2409.55
  5035.2 2411.21  5042.0 2410.47  5063.5 2410.92  5077.7 2414.85  5085.0 2415.57
  5127.0 2417.62  5141.2 2421.80  5148.6 2426.41  5173.3 2430.98  5176.7 2430.98
#Mann=5,-1,0
  4876.0    0.07       0  4916.5    0.16       0  5003.3    0.07       0
  5010.4    0.16       0  5085.0    0.07       0
Bank Sta=5003.3,5010.4
Exp/Cntr=0.3,0.1

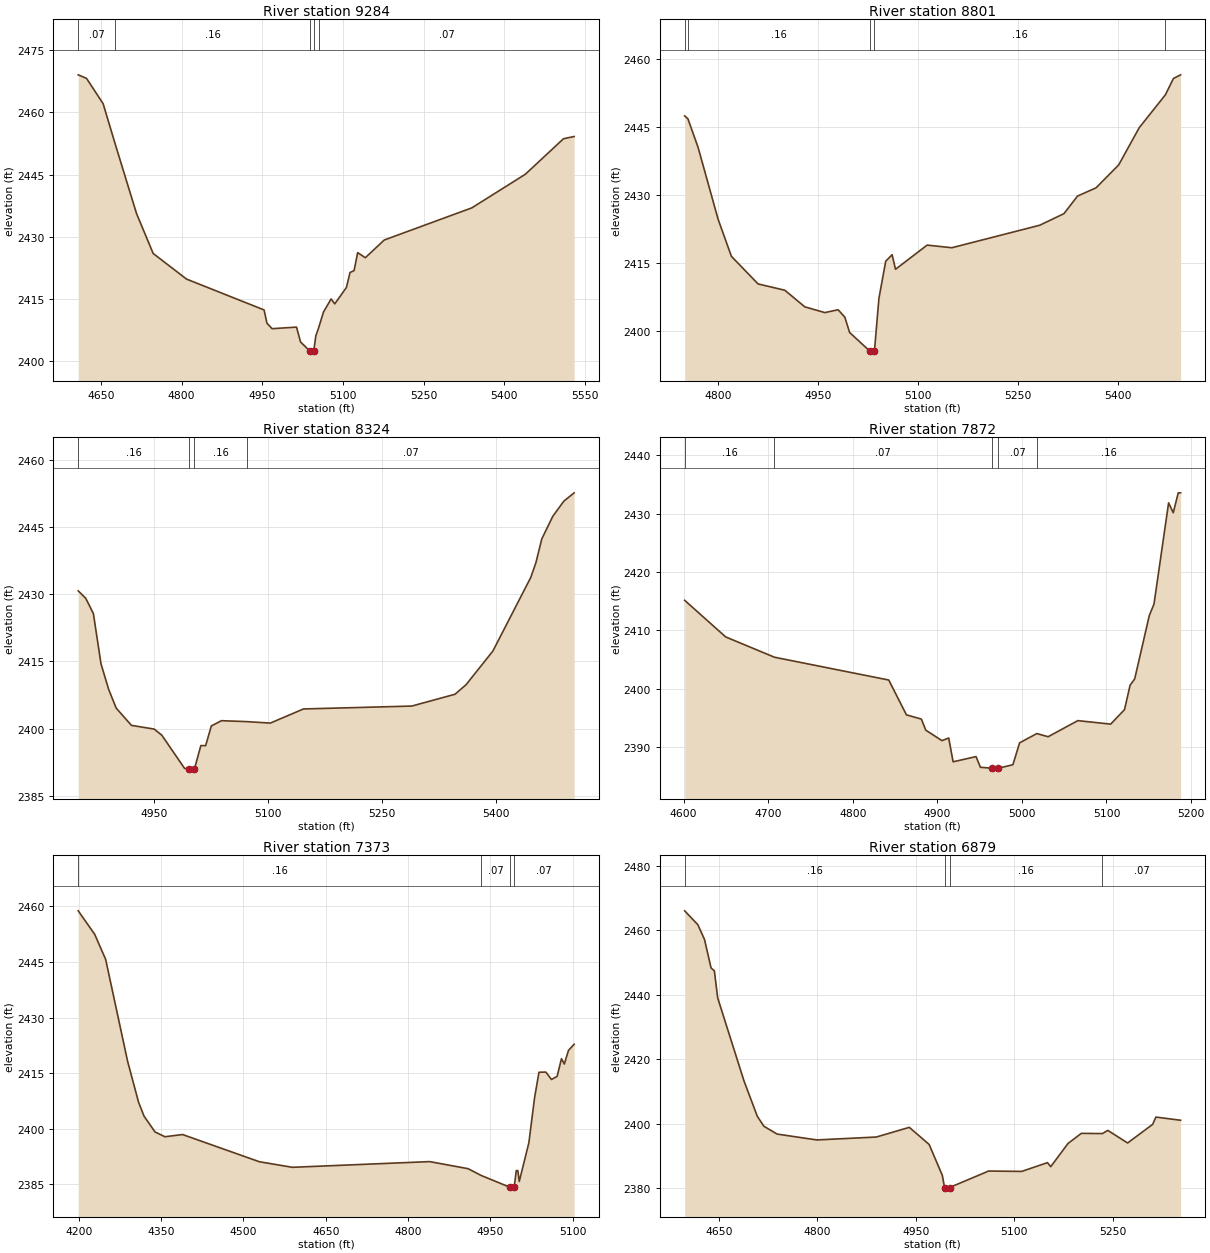
Type RM Length L Ch R = 1,9284,483,483,483
BEGIN DESCRIPTION:
Spring Creek 18.0
END DESCRIPTION:
XS GIS Cut Line= 3
      1376655.01      6803838.03      1376785.08      6804208.03
      1377179.58      6804561.82
#Sta/Elev= 30
  4607.8 2469.10  4623.3 2468.24  4654.2 2462.11  4676.9 2452.23  4716.2 2435.58
  4747.2 2425.91  4809.2 2419.72  4953.4 2412.26  4958.7 2409.07  4968.2 2407.73
  5013.7 2408.11  5021.2 2404.52  5038.5 2402.32  5039.0 2401.82  5045.7 2402.32
  5049.6 2406.00  5054.8 2407.94  5063.8 2411.74  5078.0 2414.92  5084.8 2413.73
  5106.5 2417.70  5113.2 2421.32  5120.7 2421.76  5127.4 2426.12  5141.6 2424.88
  5176.7 2429.16  5339.7 2436.94  5439.1 2445.06  5510.1 2453.65  5529.9 2454.19
#Mann=5,-1,0
  4607.8    0.07       0  4676.9    0.16       0  5038.5    0.07       0
  5045.7    0.16       0  5054.8    0.07       0
Bank Sta=5038.5,5045.7
Exp/Cntr=0.3,0.1

Type RM Length L Ch R = 1,8801,477,477,477
BEGIN DESCRIPTION:
Spring Creek 17.0
END DESCRIPTION:
XS GIS Cut Line= 3
      1376405.00      6804137.96      1376394.81      6804387.55
      1376508.82      6804868.42
#Sta/Elev= 30
  4750.2 2447.42  4755.1 2446.76  4770.3 2440.48  4800.3 2424.65  4820.3 2416.45
  4860.3 2410.36  4900.4 2408.97  4930.4 2405.31  4960.4 2404.04  4980.4 2404.66
  4990.4 2403.05  4997.7 2399.64  5027.6 2395.60  5028.1 2395.10  5034.9 2395.60
  5041.6 2407.17  5051.8 2415.37  5061.4 2416.80  5066.5 2413.59  5113.9 2418.92
  5151.0 2418.34  5282.8 2423.30  5319.1 2425.85  5339.6 2429.74  5367.3 2431.55
  5401.3 2436.60  5432.1 2444.81  5471.2 2452.03  5483.5 2455.67  5494.2 2456.47
#Mann=5,-1,0
  4750.2    0.07       0  4755.1    0.16       0  5027.6    0.07       0
  5034.9    0.16       0  5471.2    0.16       0
Bank Sta=5027.6,5034.9
Exp/Cntr=0.3,0.1

Type RM Length L Ch R = 1,8324,452,452,452
BEGIN DESCRIPTION:
Spring Creek 16.0
END DESCRIPTION:
XS GIS Cut Line= 3
      1375955.00      6804337.99      1375949.96      6804487.90
      1376254.99      6804887.98
#Sta/Elev= 30
  4850.0 2430.78  4860.0 2429.10  4870.0 2425.69  4880.0 2414.48  4890.0 2408.80
  4900.0 2404.57  4920.1 2400.70  4950.1 2399.87  4960.1 2398.50  4990.1 2391.08
  4995.6 2390.97  4996.1 2390.47  5003.1 2390.97  5011.5 2396.19  5017.8 2396.16
  5025.3 2400.57  5038.6 2401.75  5071.8 2401.54  5103.0 2401.21  5146.6 2404.37
  5289.3 2405.02  5346.2 2407.66  5360.7 2409.78  5396.1 2417.33  5446.0 2433.79
  5452.8 2437.11  5460.5 2442.40  5475.0 2447.46  5489.6 2450.85  5503.1 2452.70
#Mann=4,-1,0
  4850.0    0.16       0  4995.6    0.07       0  5003.1    0.16       0
  5071.8    0.07       0
Bank Sta=4995.6,5003.1
Exp/Cntr=0.3,0.1

Type RM Length L Ch R = 1,7872,499,499,499
BEGIN DESCRIPTION:
Spring Creek 15.0
END DESCRIPTION:
XS GIS Cut Line= 3
      1375655.00      6804437.99      1375775.28      6804818.11
      1375855.02      6804988.03
#Sta/Elev= 30
  4601.3 2415.14  4649.8 2408.86  4707.5 2405.38  4842.6 2401.47  4863.5 2395.50
  4881.2 2394.77  4886.4 2392.87  4905.5 2391.08  4913.5 2391.53  4918.7 2387.45
  4945.8 2388.34  4951.0 2386.51  4964.7 2386.35  4965.2 2385.85  4972.2 2386.35
  4989.4 2386.95  4997.3 2390.70  5017.7 2392.29  5031.1 2391.75  5066.2 2394.51
  5105.0 2393.91  5121.4 2396.40  5127.9 2400.56  5133.4 2401.66  5150.7 2412.54
  5156.2 2414.47  5173.5 2431.85  5179.0 2430.16  5184.9 2433.57  5187.7 2433.57
#Mann=5,-1,0
  4601.3    0.16       0  4707.5    0.07       0  4964.7    0.07       0
  4972.2    0.07       0  5017.7    0.16       0
Bank Sta=4964.7,4972.2
Exp/Cntr=0.3,0.1

Type RM Length L Ch R = 1,7373,494,494,494
BEGIN DESCRIPTION:
Spring Creek 14.0
END DESCRIPTION:
XS GIS Cut Line= 3
      1375405.00      6804288.02      1375429.87      6805088.54
      1375455.00      6805188.01
#Sta/Elev= 30
  4199.1 2458.82  4229.1 2452.49  4249.1 2445.72  4289.1 2418.20  4309.1 2407.13
  4319.1 2403.37  4339.1 2399.12  4357.1 2397.83  4389.2 2398.43  4529.2 2391.08
  4589.3 2389.58  4839.4 2391.12  4909.4 2389.21  4933.2 2387.38  4985.7 2384.19
  4986.2 2383.69  4993.3 2384.19  4997.2 2388.70  5000.0 2388.70  5002.6 2385.76
  5020.1 2396.20  5030.4 2408.26  5038.5 2415.24  5051.0 2415.29  5061.3 2413.29
  5071.6 2414.14  5079.5 2418.91  5084.7 2417.46  5092.3 2421.15  5102.6 2422.80
#Mann=4,-1,0
  4199.1    0.16       0  4933.2    0.07       0  4985.7    0.07       0
  4993.3    0.07       0
Bank Sta=4985.7,4993.3
Exp/Cntr=0.3,0.1

Type RM Length L Ch R = 1,6879,500,500,500
BEGIN DESCRIPTION:
Spring Creek 13.0
END DESCRIPTION:
XS GIS Cut Line= 3
      1375305.00      6804288.02      1375260.57      6804687.35
      1375305.01      6805038.05
#Sta/Elev= 30
  4598.2 2466.06  4618.3 2461.74  4628.4 2457.16  4638.4 2448.31  4643.4 2447.43
  4648.5 2439.01  4688.7 2413.13  4708.9 2402.21  4718.9 2399.14  4739.0 2396.72
  4799.4 2394.90  4890.0 2395.80  4940.3 2398.81  4970.5 2393.50  4990.6 2383.89
  4994.0 2380.12  4994.5 2379.62  5001.6 2380.12  5061.1 2385.24  5111.5 2385.12
  5150.7 2387.85  5155.7 2386.60  5182.1 2393.82  5202.3 2396.94  5234.5 2396.88
  5242.6 2397.87  5272.8 2393.95  5310.9 2399.74  5315.9 2402.00  5353.5 2401.01
#Mann=4,-1,0
  4598.2    0.16       0  4994.0    0.07       0  5001.6    0.16       0
  5234.5    0.07       0
Bank Sta=4994,5001.6
Exp/Cntr=0.3,0.1

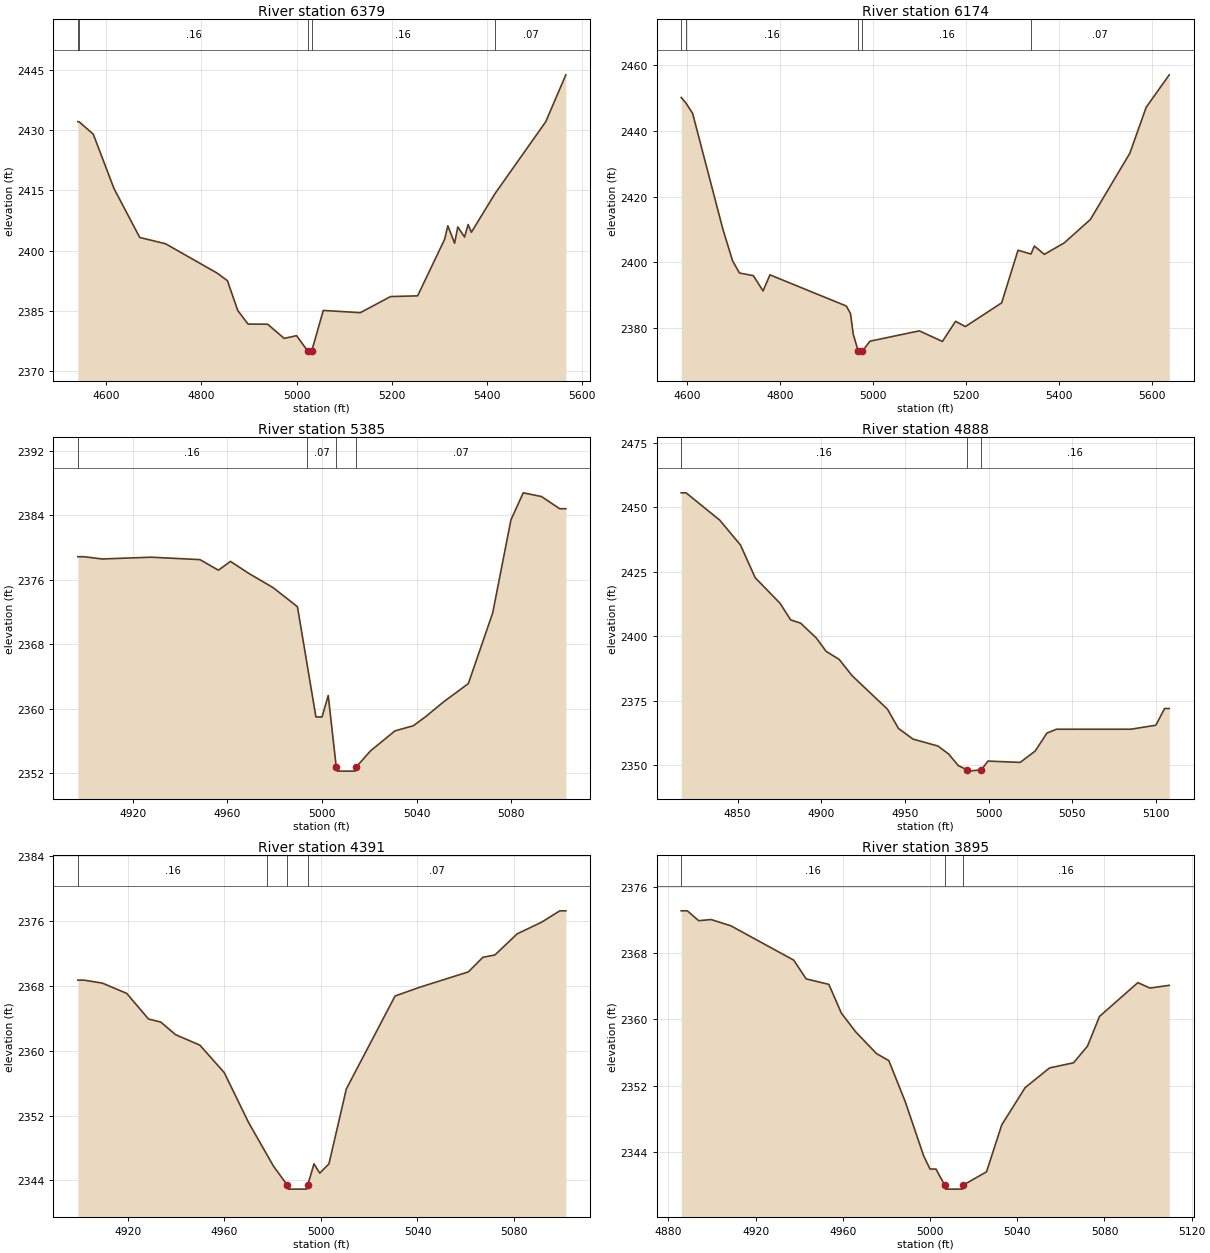
Type RM Length L Ch R = 1,6379,205,205,205
BEGIN DESCRIPTION:
Spring Creek 12.0
END DESCRIPTION:
XS GIS Cut Line= 3
      1374604.99      6804838.00      1375028.95      6805015.19
      1375404.97      6805437.96
#Sta/Elev= 30
  4540.5 2432.09  4543.3 2432.07  4573.0 2428.98  4616.4 2415.48  4670.6 2403.27
  4724.8 2401.71  4833.1 2394.41  4854.8 2392.52  4876.5 2385.10  4898.2 2381.71
  4939.3 2381.68  4974.0 2378.15  5000.0 2378.83  5023.7 2374.98  5024.2 2374.48
  5031.8 2374.98  5056.2 2385.11  5134.0 2384.55  5197.5 2388.56  5254.4 2388.74
  5311.2 2402.83  5317.9 2406.18  5332.1 2401.85  5338.8 2405.89  5353.0 2403.38
  5360.6 2406.49  5367.3 2404.56  5416.8 2414.16  5523.6 2432.09  5565.8 2443.76
#Mann=5,-1,0
  4540.5    0.07       0  4543.3    0.16       0  5023.7    0.07       0
  5031.8    0.16       0  5416.8    0.07       0
Bank Sta=5023.7,5031.8
Exp/Cntr=0.3,0.1

Type RM Length L Ch R = 1,6174,789,789,789
BEGIN DESCRIPTION:
Spring Creek 11.0
END DESCRIPTION:
XS GIS Cut Line= 3
      1374524.86      6804893.31      1374864.63      6805127.20
      1375305.01      6805588.01
#Sta/Elev= 30
  4587.5 2450.11  4597.6 2448.41  4612.0 2445.27  4676.9 2410.18  4697.9 2400.49
  4712.8 2396.76  4742.6 2395.96  4763.5 2391.33  4778.4 2396.20  4942.7 2386.72
  4951.6 2384.46  4957.6 2378.14  4968.5 2372.91  4969.0 2372.41  4976.6 2372.91
  4993.5 2376.04  5099.7 2379.18  5149.4 2375.96  5177.7 2382.08  5198.8 2380.48
  5276.8 2387.68  5312.0 2403.67  5339.9 2402.53  5347.2 2404.96  5368.6 2402.43
  5411.1 2405.88  5467.7 2413.02  5552.6 2433.16  5587.8 2447.15  5637.4 2456.99
#Mann=5,-1,0
  4587.5    0.07       0  4597.6    0.16       0  4968.5    0.07       0
  4976.6    0.16       0  5339.9    0.07       0
Bank Sta=4968.5,4976.6
Exp/Cntr=0.3,0.1

Type RM Length L Ch R = 1,5385,497,497,497
BEGIN DESCRIPTION:
Spring Creek 10.0
END DESCRIPTION:
XS GIS Cut Line= 3
      1374605.01      6805387.97      1374580.03      6805488.10
      1374555.00      6805588.01
#Sta/Elev= 30
  4896.8 2378.87  4899.4 2378.87  4907.1 2378.59  4927.8 2378.81  4948.4 2378.51
  4956.2 2377.20  4961.3 2378.29  4969.0 2376.81  4979.3 2375.04  4989.6 2372.67
  4993.5 2365.84  4997.4 2359.01  5000.0 2359.01  5002.6 2361.67  5006.0 2352.79
  5006.5 2352.29  5013.9 2352.29  5014.4 2352.79  5020.5 2354.81  5030.8 2357.28
  5038.6 2357.92  5043.8 2359.05  5051.4 2360.89  5061.8 2363.14  5072.1 2371.91
  5079.8 2383.44  5085.0 2386.79  5092.7 2386.33  5100.4 2384.82  5103.0 2384.82
#Mann=4,-1,0
  4896.8    0.16       0  4993.5    0.07       0  5006.0    0.07       0
  5014.4    0.07       0
Bank Sta=5006,5014.4
Exp/Cntr=0.3,0.1

Type RM Length L Ch R = 1,4888,497,497,497
BEGIN DESCRIPTION:
Spring Creek 9.0
END DESCRIPTION:
XS GIS Cut Line= 3
      1374055.00      6805238.01      1374152.45      6805393.73
      1374204.99      6805487.98
#Sta/Elev= 30
  4816.3 2455.51  4819.2 2455.51  4839.3 2444.93  4851.7 2435.29  4860.5 2422.60
  4875.3 2412.73  4881.7 2406.25  4887.6 2405.01  4897.0 2399.25  4902.9 2394.05
  4910.7 2390.92  4918.3 2384.69  4939.5 2371.67  4946.1 2364.17  4954.8 2360.05
  4969.7 2357.35  4976.0 2354.32  4981.9 2349.73  4987.2 2348.13  4987.7 2347.63
  4995.6 2348.13  4999.6 2351.53  5018.8 2351.01  5027.8 2355.41  5034.8 2362.38
  5040.5 2363.87  5085.0 2363.88  5099.9 2365.43  5105.1 2371.91  5107.9 2371.91
#Mann=3,-1,0
  4816.3    0.16       0  4987.2    0.07       0  4995.6    0.16       0
Bank Sta=4987.2,4995.6
Exp/Cntr=0.3,0.1

Type RM Length L Ch R = 1,4391,496,496,496
BEGIN DESCRIPTION:
Spring Creek 8.0
END DESCRIPTION:
XS GIS Cut Line= 3
      1373805.01      6805587.96      1373789.84      6805687.61
      1373805.00      6805787.98
#Sta/Elev= 29
  4899.2 2368.73  4901.8 2368.73  4909.4 2368.36  4919.5 2367.09  4928.5 2363.93
  4933.6 2363.55  4939.7 2362.00  4949.8 2360.70  4959.9 2357.31  4970.0 2351.14
  4977.7 2347.12  4980.2 2345.81  4986.0 2343.42  4986.5 2342.92  4994.0 2342.92
  4994.5 2343.42  4997.1 2346.04  4999.5 2344.90  5003.3 2346.04  5010.5 2355.29
  5030.7 2366.77  5040.8 2367.84  5061.1 2369.75  5067.1 2371.55  5072.1 2371.84
  5081.3 2374.44  5091.4 2375.88  5099.0 2377.29  5101.5 2377.29
#Mann=4,-1,0
  4899.2    0.16       0  4977.7    0.07       0  4986.0    0.07       0
  4994.5    0.07       0
Bank Sta=4986,4994.5
Exp/Cntr=0.3,0.1

Type RM Length L Ch R = 1,3895,436,436,436
BEGIN DESCRIPTION:
Spring Creek 7.0
END DESCRIPTION:
XS GIS Cut Line= 3
      1373255.01      6805538.02      1373310.00      6805638.00
      1373355.02      6805738.04
#Sta/Elev= 30
  4885.9 2373.10  4888.7 2373.10  4893.9 2371.91  4899.6 2372.05  4908.7 2371.29
  4937.5 2367.15  4943.2 2364.89  4953.6 2364.23  4959.3 2360.78  4965.8 2358.53
  4975.4 2355.89  4981.1 2355.03  4988.6 2350.10  4997.1 2343.53  5000.0 2341.95
  5002.7 2341.95  5006.7 2340.03  5007.2 2339.53  5014.8 2339.53  5015.3 2340.03
  5025.9 2341.62  5032.9 2347.29  5043.6 2351.77  5054.8 2354.15  5065.8 2354.77
  5072.2 2356.78  5077.7 2360.36  5095.3 2364.44  5100.8 2363.79  5109.7 2364.11
#Mann=3,-1,0
  4885.9    0.16       0  5006.7    0.07       0  5015.3    0.16       0
Bank Sta=5006.7,5015.3
Exp/Cntr=0.3,0.1