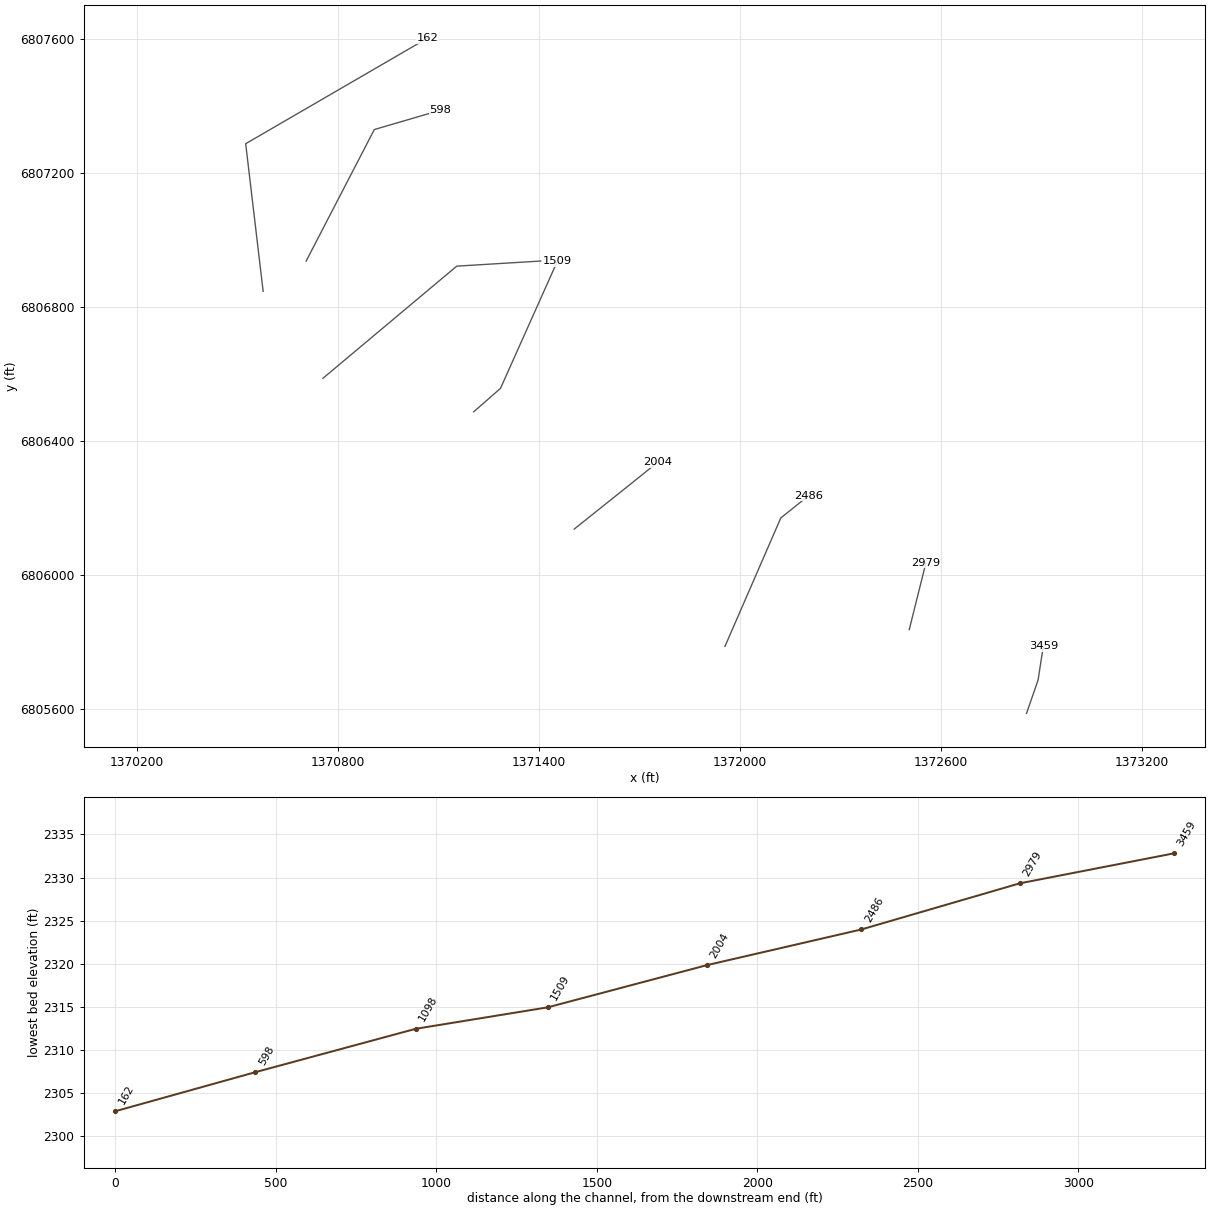
HEC-RAS study Spring Creek.prj: Spring Creek Base Level Engineering

--- Spring Creek.g01 (geometry) --- (continued)

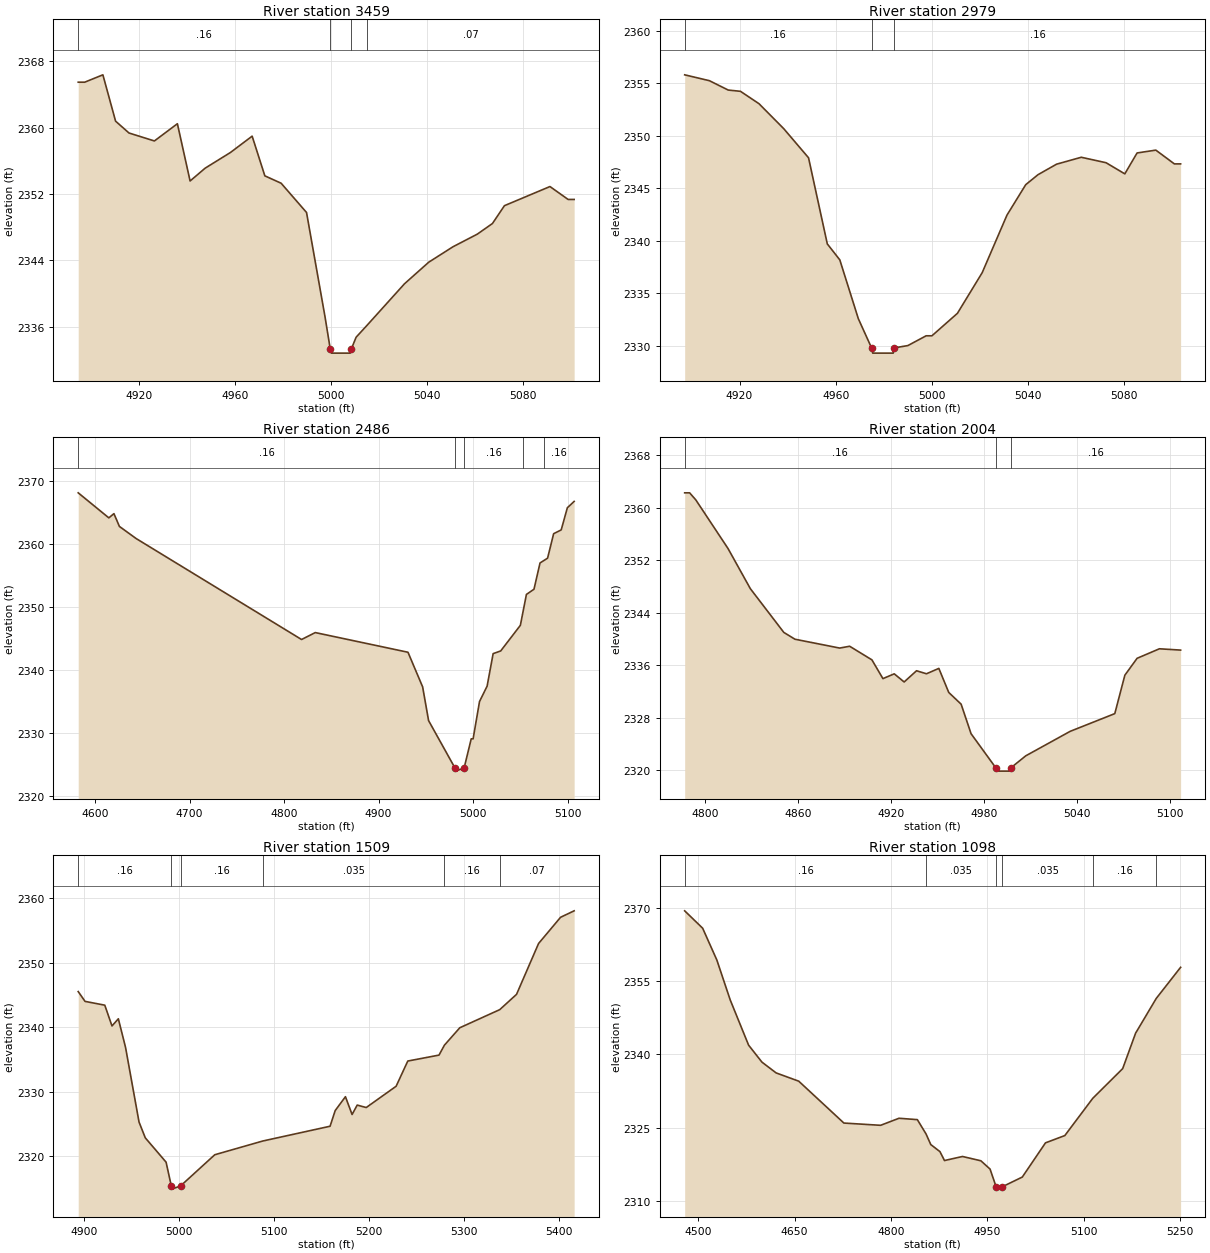
Type RM Length L Ch R = 1,3459,480,480,480
BEGIN DESCRIPTION:
Spring Creek 6.0
END DESCRIPTION:
XS GIS Cut Line= 3
      1372854.99      6805587.97      1372889.57      6805687.65
      1372904.99      6805787.97
#Sta/Elev= 30
  4894.5 2365.49  4897.2 2365.49  4904.8 2366.38  4910.1 2360.79  4915.7 2359.36
  4926.3 2358.40  4935.9 2360.48  4941.2 2353.57  4947.5 2355.12  4958.0 2357.00
  4967.1 2358.98  4972.4 2354.19  4979.2 2353.30  4989.8 2349.77  4997.5 2337.21
  4999.7 2333.30  5000.2 2332.80  5008.0 2332.80  5008.5 2333.30  5010.5 2334.72
  5015.1 2336.17  5030.7 2341.17  5040.8 2343.77  5050.9 2345.63  5061.1 2347.16
  5067.4 2348.44  5072.4 2350.59  5091.4 2352.90  5099.0 2351.34  5101.5 2351.34
#Mann=4,-1,0
  4894.5    0.16       0  4999.7    0.07       0  5008.5    0.16       0
  5015.1    0.07       0
Bank Sta=4999.7,5008.5
Exp/Cntr=0.3,0.1

Type RM Length L Ch R = 1,2979,493,493,493
BEGIN DESCRIPTION:
Spring Creek 5.0
END DESCRIPTION:
XS GIS Cut Line= 3
      1372505.00      6805837.99      1372529.89      6805937.73
      1372555.01      6806038.03
#Sta/Elev= 30
  4897.2 2355.82  4907.5 2355.26  4915.3 2354.37  4920.4 2354.25  4928.1 2353.07
  4938.4 2350.69  4948.7 2347.92  4956.5 2339.72  4961.7 2338.20  4969.4 2332.60
  4974.9 2329.82  4975.4 2329.32  4983.9 2329.32  4984.4 2329.82  4990.0 2330.04
  4997.6 2330.97  5000.0 2330.97  5010.6 2333.11  5020.9 2336.98  5031.2 2342.46
  5039.0 2345.36  5044.1 2346.31  5051.8 2347.31  5062.1 2347.97  5072.4 2347.45
  5080.2 2346.39  5085.3 2348.38  5093.1 2348.65  5100.8 2347.34  5103.4 2347.34
#Mann=3,-1,0
  4897.2    0.16       0  4974.9    0.07       0  4984.4    0.16       0
Bank Sta=4974.9,4984.4
Exp/Cntr=0.3,0.1

Type RM Length L Ch R = 1,2486,482,482,482
BEGIN DESCRIPTION:
Spring Creek 4.0
END DESCRIPTION:
XS GIS Cut Line= 3
      1371955.02      6805788.04      1372121.61      6806171.19
      1372205.04      6806238.03
#Sta/Elev= 30
  4582.2 2368.10  4614.6 2364.13  4620.0 2364.80  4625.8 2362.77  4643.5 2360.85
  4818.5 2344.84  4833.0 2345.94  4931.1 2342.82  4946.6 2337.33  4952.9 2331.98
  4980.8 2324.47  4981.3 2323.97  4990.5 2324.47  4998.0 2329.09  5000.0 2329.09
  5006.8 2335.01  5014.8 2337.44  5021.2 2342.60  5029.2 2343.03  5050.0 2347.09
  5053.1 2349.46  5056.4 2351.99  5064.4 2352.81  5070.8 2356.98  5074.5 2357.33
  5078.8 2357.74  5085.2 2361.62  5093.2 2362.22  5099.7 2365.73  5106.9 2366.74
#Mann=5,-1,0
  4582.2    0.16       0  4980.8    0.07       0  4990.5    0.16       0
  5053.1    0.07       0  5074.5    0.16       0
Bank Sta=4980.8,4990.5
Exp/Cntr=0.3,0.1

Type RM Length L Ch R = 1,2004,495,495,495
BEGIN DESCRIPTION:
Spring Creek 3.0
END DESCRIPTION:
XS GIS Cut Line= 3
      1371505.00      6806138.00      1371671.52      6806270.98
      1371755.04      6806338.03
#Sta/Elev= 30
  4786.9 2362.27  4790.1 2362.27  4794.1 2361.19  4814.9 2353.77  4829.3 2347.65
  4850.9 2340.98  4858.1 2339.94  4887.0 2338.59  4893.4 2338.87  4907.8 2336.79
  4914.9 2333.93  4922.2 2334.66  4928.6 2333.42  4936.6 2335.13  4943.0 2334.67
  4951.0 2335.49  4957.4 2331.82  4965.4 2330.03  4971.8 2325.53  4987.8 2320.32
  4988.3 2319.82  4997.0 2319.82  4997.5 2320.32  5007.1 2322.15  5035.8 2325.89
  5064.6 2328.59  5071.1 2334.45  5079.0 2337.03  5093.4 2338.48  5107.1 2338.28
#Mann=3,-1,0
  4786.9    0.16       0  4987.8    0.07       0  4997.5    0.16       0
Bank Sta=4987.8,4997.5
Exp/Cntr=0.3,0.1

Type RM Length L Ch R = 1,1509,411,411,411
BEGIN DESCRIPTION:
Spring Creek 2.0
END DESCRIPTION:
XS GIS Cut Line= 3
      1371204.97      6806487.97      1371284.96      6806557.98
      1371454.99      6806937.98
#Sta/Elev= 30
  4893.7 2345.56  4900.9 2344.04  4921.7 2343.45  4929.3 2340.23  4936.0 2341.34
  4943.6 2336.89  4957.8 2325.33  4964.4 2322.88  4986.3 2319.11  4991.8 2315.43
  4992.3 2314.93  5001.6 2315.43  5037.6 2320.26  5088.2 2322.39  5159.1 2324.68
  5164.5 2327.11  5175.3 2329.26  5182.3 2326.50  5187.7 2327.96  5197.2 2327.58
  5228.7 2330.88  5241.0 2334.79  5273.9 2335.71  5279.6 2337.25  5295.8 2339.95
  5337.9 2342.76  5355.6 2345.13  5378.8 2353.01  5402.0 2357.08  5416.3 2358.08
#Mann=6,-1,0
  4893.7    0.16       0  4991.8    0.07       0  5001.6    0.16       0
  5088.2   0.035       0  5279.6    0.16       0  5337.9    0.07       0
Bank Sta=4991.8,5001.6
Exp/Cntr=0.3,0.1

Type RM Length L Ch R = 1,1098,500,500,500
BEGIN DESCRIPTION:
Spring Creek 1.0
END DESCRIPTION:
XS GIS Cut Line= 3
      1370755.01      6806588.01      1371154.48      6806922.78
      1371405.02      6806938.00
#Sta/Elev= 30
  4478.8 2369.39  4506.8 2365.83  4528.9 2359.32  4549.7 2351.16  4578.3 2341.91
  4599.1 2338.43  4621.2 2336.22  4656.4 2334.53  4726.7 2325.96  4783.9 2325.50
  4812.5 2326.94  4841.1 2326.66  4854.7 2323.71  4862.0 2321.56  4876.3 2320.11
  4883.3 2318.29  4911.4 2319.12  4940.0 2318.24  4954.3 2316.54  4963.7 2312.94
  4964.2 2312.44  4973.6 2312.94  5004.5 2314.91  5040.6 2321.91  5070.7 2323.40
  5114.2 2331.02  5160.8 2337.10  5180.9 2344.35  5213.1 2351.47  5251.0 2357.83
#Mann=6,-1,0
  4478.8    0.16       0  4854.7   0.035       0  4963.7   0.035       0
  4973.6   0.035       0  5114.2    0.16       0  5213.1    0.07       0
Bank Sta=4963.7,4973.6
Exp/Cntr=0.3,0.1

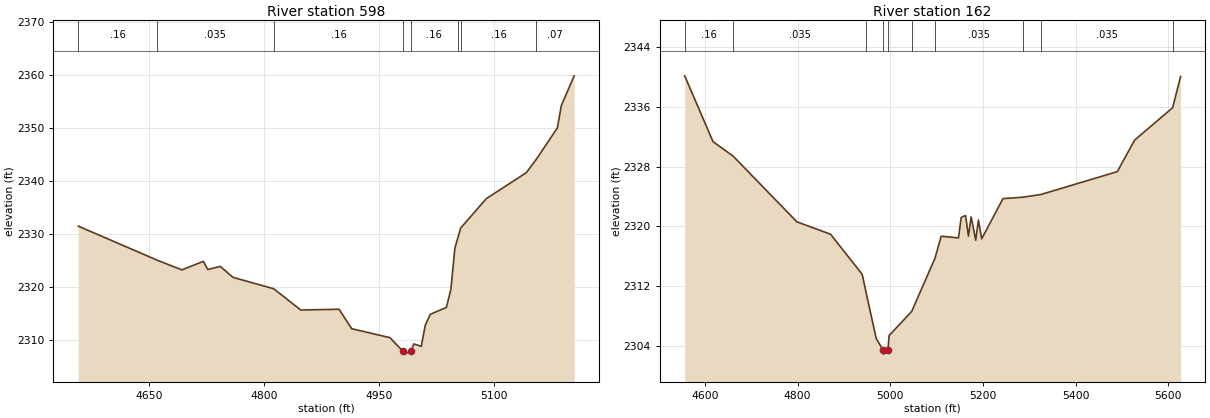
Type RM Length L Ch R = 1,598,436,436,436
BEGIN DESCRIPTION:
Sweetwater Creek Trib 8 40.0
END DESCRIPTION:
XS GIS Cut Line= 3
      1370704.99      6806937.97      1370908.35      6807330.41
      1371104.99      6807388.00
#Sta/Elev= 30
  4558.0 2331.57  4660.9 2325.14  4693.2 2323.30  4721.2 2324.92  4727.0 2323.37
  4743.3 2323.96  4759.8 2321.90  4813.0 2319.74  4848.3 2315.73  4898.2 2315.87
  4914.7 2312.20  4964.6 2310.51  4981.8 2307.90  4982.3 2307.40  4991.7 2307.90
  4995.8 2309.32  5005.5 2308.87  5010.7 2312.86  5017.3 2314.92  5038.2 2316.21
  5044.1 2319.60  5049.3 2327.39  5053.3 2329.41  5056.8 2331.18  5090.3 2336.75
  5142.4 2341.64  5155.6 2344.19  5183.0 2350.10  5188.2 2354.33  5204.9 2359.93
#Mann=8,-1,0
  4558.0    0.16       0  4660.9   0.035       0  4813.0    0.16       0
  4981.8    0.07       0  4991.7    0.16       0  5053.3    0.07       0
  5056.8    0.16       0  5155.6    0.07       0
Bank Sta=4981.8,4991.7
Exp/Cntr=0.3,0.1

Type RM Length L Ch R = 1,162,0,0,0
BEGIN DESCRIPTION:
Spring Creek 4367
END DESCRIPTION:
XS GIS Cut Line= 3
      1370576.64      6806847.53      1370524.52      6807288.16
      1371066.22      6807602.70
#Sta/Elev= 30
  4556.3 2340.17  4617.5 2331.34  4660.5 2329.43  4798.4 2320.60  4871.1 2318.94
  4939.4 2313.56  4947.9 2311.08  4969.6 2304.96  4984.8 2303.37  4985.3 2302.87
  4994.8 2303.37  4997.4 2305.36  5046.3 2308.61  5096.3 2315.71  5109.8 2318.67
  5147.1 2318.45  5152.9 2321.19  5162.4 2321.45  5168.6 2318.68  5174.4 2321.27
  5184.3 2318.14  5190.1 2320.84  5197.1 2318.32  5243.1 2323.71  5286.1 2323.90
  5324.6 2324.26  5489.8 2327.33  5527.1 2331.55  5609.2 2335.90  5626.4 2340.08
#Mann=10,-1,0
  4556.3    0.16       0  4660.5   0.035       0  4947.9   0.063       0
  4984.8   0.063       0  4994.8   0.063       0  5046.3    0.16       0
  5096.3   0.035       0  5286.1    0.07       0  5324.6   0.035       0
  5609.2    0.16       0
Bank Sta=4984.8,4994.8
Exp/Cntr=0.3,0.1

Chan Stop Cuts=-1