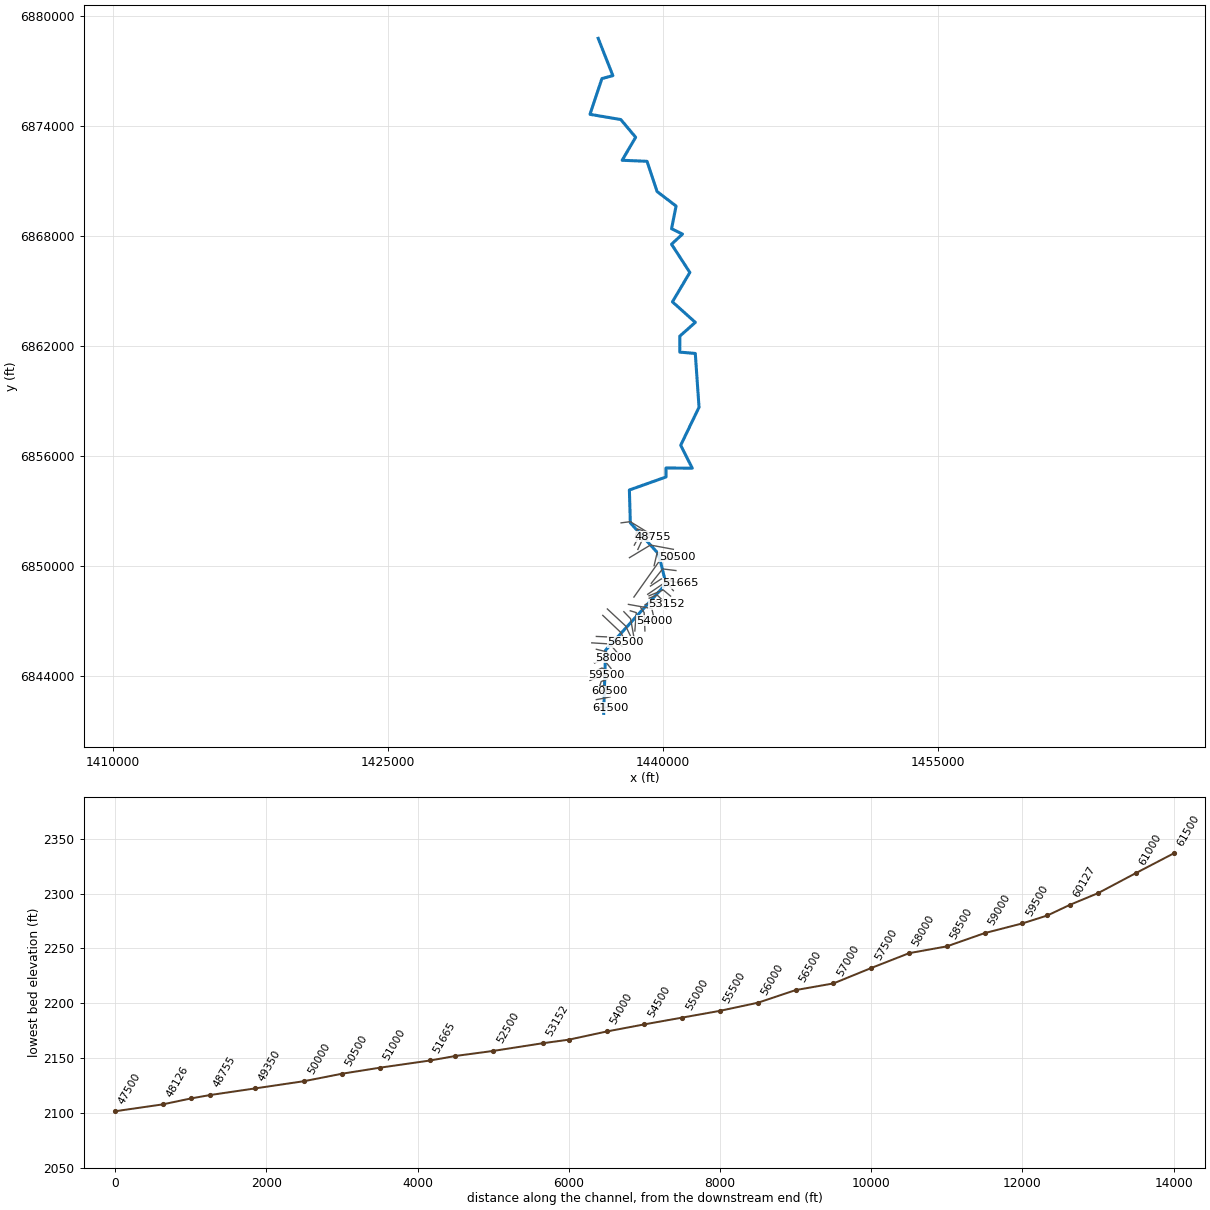
--- Stink Creek.prj (project) ---

Proj Title=Stink Creek Base Level Engineering
Current Plan=p01
Default Exp/Contr=0.3,0.1
English Units
Geom File=g01
Flow File=f01
Plan File=p01
Y Axis Title=Elevation
X Axis Title(PF)=Main Channel Distance
X Axis Title(XS)=Station
BEGIN DESCRIPTION:
Stink Creek
END DESCRIPTION:
DSS Export Rating Curves= 0
DSS Export Rating Curve Sorted= 0
DSS Export Volume Flow Curves= 0
DXF OffsetX= 0
DXF OffsetY= 0
DXF ScaleX= 1
DXF ScaleY= 10

--- Stink Creek.p01 (plan) ---

Plan Title=Multiple Run
Short Identifier=Multiple
Geom File=g01
Flow File=f01
Subcritical Flow
K Sum by GR= 0
Std Step Tol= 0.01
Critical Tol= 0.01
Num of Std Step Trials= 20
Max Error Tol= 0.3
Flow Tol Ratio= 0.001
Split Flow NTrial= 30
Split Flow Tol= 0.02
Split Flow Ratio= 0.02
Log Output Level= 0
Friction Slope Method= 1
Unsteady Friction Slope Method= 2
Unsteady Bridges Friction Slope Method= 1
Parabolic Critical Depth
Global Vel Dist=  1 , 1 , 1
Global Log Level= 0
CheckData=True
Encroach Param= -1, 0, 0, 0
BEGIN DESCRIPTION:
Multiple Run
END DESCRIPTION:

--- Stink Creek.f01 (steady flow) ---

Flow Title=Multiple
Number of Profiles=7
Profile Names=10-year,25-year,50-year,1pct_min,100-year,1pct_plu,500-year
River Rch & RM= Stink Creek,Reach-1,61500
     218     310     389     244     487     972     771
River Rch & RM= Stink Creek,Reach-1,59831
     625     944    1230     798    1592    3176    2698
River Rch & RM= Stink Creek,Reach-1,53500
     916    1410    1861    1221    2435    4859    4226
River Rch & RM= Stink Creek,Reach-1,47500
    1087    1684    2232    1469    2931    5849    5124
River Rch & RM= Stink Creek,Reach-1,46000
    1035    1586    2085    1360    2714    5416    4662
River Rch & RM= Stink Creek,Reach-1,40500
    1040    1581    2068    1341    2676    5340    4544
River Rch & RM= Stink Creek,Reach-1,34699
    1057    1598    2081    1343    2680    5347    4505
River Rch & RM= Stink Creek,Reach-1,25823
    1145    1733    2259    1459    2911    5809    4901
River Rch & RM= Stink Creek,Reach-1,21500
    1112    1675    2175    1399    2792    5571    4664
River Rch & RM= Stink Creek,Reach-1,13000
    1222    1843    2395    1542    3076    6137    5141
River Rch & RM= Stink Creek,Reach-1,6000
    2018    3099    4079    2655    5297   10569    9054
River Rch & RM= Stink Creek,Reach-1,3500
    2216    3408    4490    2924    5834   11641    9985
Boundary for River Rch & Prof#=Stink Creek,Reach-1,1
Up Type=0
Dn Type=3
Dn Slope=0.005
Boundary for River Rch & Prof#=Stink Creek,Reach-1,2
Up Type=0
Dn Type=3
Dn Slope=0.005
Boundary for River Rch & Prof#=Stink Creek,Reach-1,3
Up Type=0
Dn Type=3
Dn Slope=0.005
Boundary for River Rch & Prof#=Stink Creek,Reach-1,4
Up Type=0
Dn Type=3
Dn Slope=0.005
Boundary for River Rch & Prof#=Stink Creek,Reach-1,5
Up Type=0
Dn Type=3
Dn Slope=0.005
Boundary for River Rch & Prof#=Stink Creek,Reach-1,6
Up Type=0
Dn Type=3
Dn Slope=0.005
Boundary for River Rch & Prof#=Stink Creek,Reach-1,7
Up Type=0
Dn Type=3
Dn Slope=0.005

--- Stink Creek.g01 (geometry) ---

Geom Title=Existing Conditions
Program Version=4.10

River Reach=Stink Creek     ,Reach-1
Reach XY= 30
        1436755.        6841938.      1436858.55      6845386.53
      1440154.51      6849003.22      1439749.18      6850640.31
      1438208.55      6852339.47      1438156.96      6854132.13
      1440157.59      6854843.71      1440156.62      6855334.88
      1441588.85      6855321.43      1440955.01      6856572.59
      1441955.46      6858648.18      1441752.01       6861586.6
      1440904.49      6861658.23      1440907.91      6862530.09
      1441753.04      6863282.11       1440505.5      6864403.22
      1441455.52      6866008.04      1440455.55      6867548.63
      1441055.05      6868103.34      1440456.91      6868393.98
      1440702.77       6869632.1      1439665.95      6870427.98
      1439118.74       6872074.8      1437762.45      6872131.93
      1438497.69       6873387.9      1437688.75      6874355.31
      1436007.73      6874639.87      1436659.95      6876590.58
      1437255.19      6876753.29        1436455.        6878788.

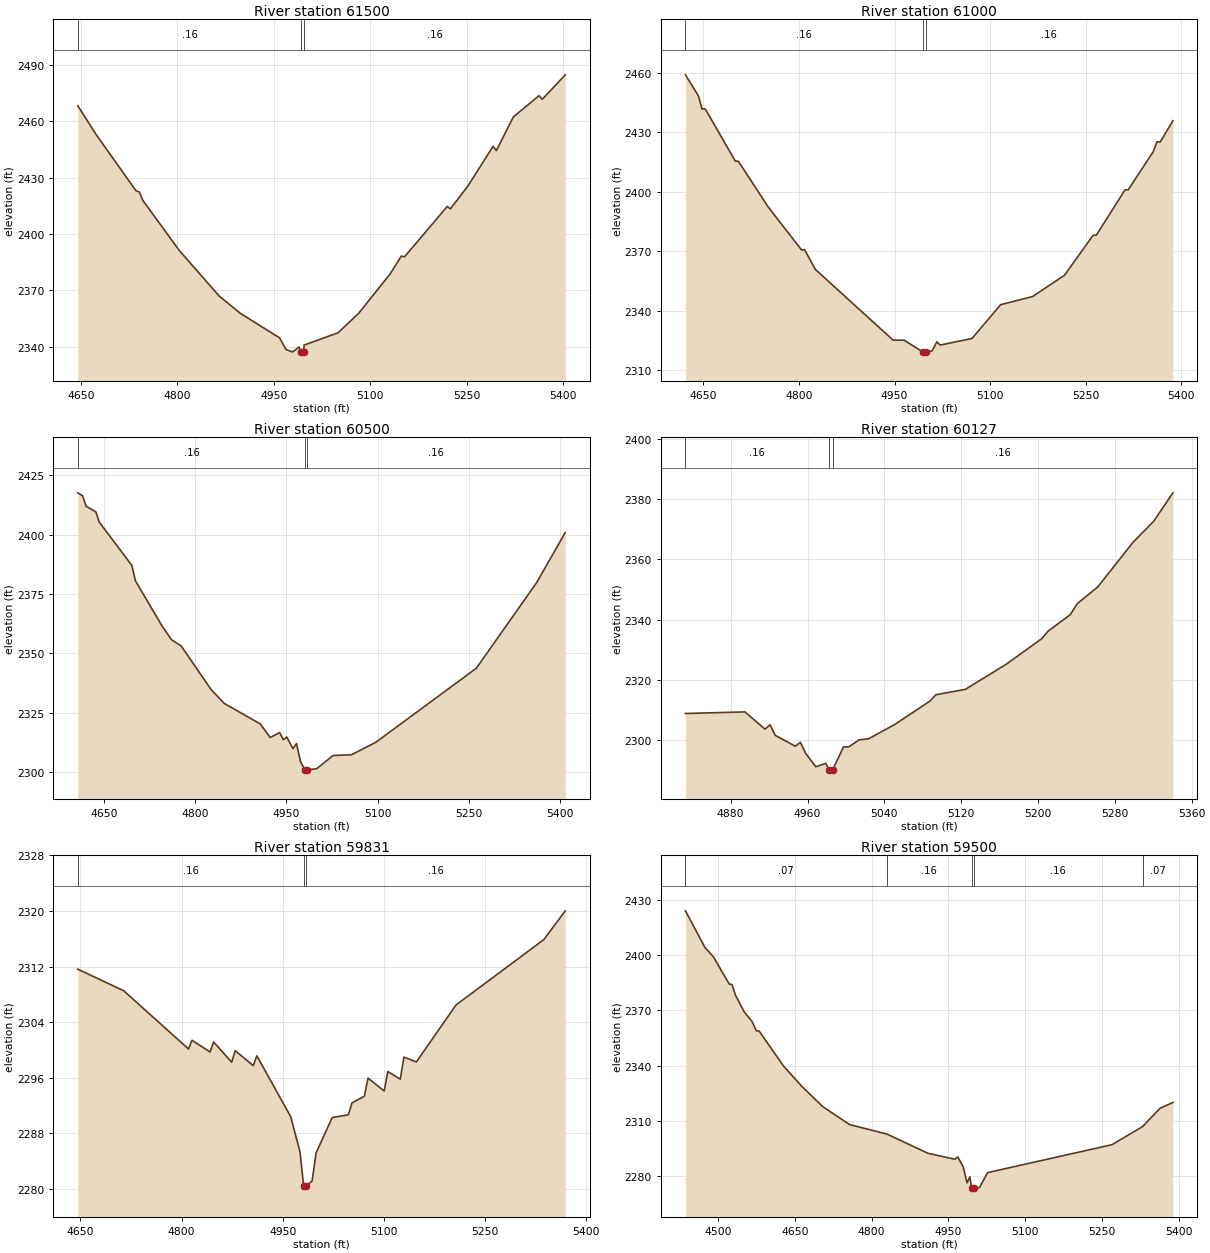
Type RM Length L Ch R = 1 ,61500   ,500,500,500
BEGIN DESCRIPTION:
Stink Creek 115.0
END DESCRIPTION:
XS GIS Cut Line= 3
      1436355.02        6842238.      1436705.39       6842293.9
        1437105.        6842238.
#Sta/Elev= 30
  4645.2 2468.23  4673.7 2452.93  4735.8    2423  4740.9 2422.32  4746.4 2417.87
    4803 2391.28  4865.1 2366.98  4898.3 2357.72  4959.1 2344.74  4969.2  2338.5
  4979.3 2337.22  4989.4 2339.84  4992.4  2337.1  4992.7  2336.6  4996.4  2337.1
  4997.3 2340.89  5050.1 2347.43    5082 2357.75  5130.9 2378.65  5148.4 2388.21
  5153.5 2387.86  5219.9 2414.65  5224.9 2413.39    5252  2425.5  5291.3  2446.7
  5296.3 2444.38  5322.7 2462.26  5362.7 2473.61  5367.8 2471.69  5403.5 2484.69
#Mann= 3 ,-1 , 0
  4645.2     .16       0  4992.4     .07       0  4996.4     .16       0
Bank Sta=4992.4,4996.4
XS Rating Curve= 0 ,0
Exp/Cntr=0.3,0.1

Type RM Length L Ch R = 1 ,61000   ,500,500,500
BEGIN DESCRIPTION:
Stink Creek 114.0
END DESCRIPTION:
XS GIS Cut Line= 3
      1436354.98        6842688.      1436726.42       6842759.2
      1437105.01        6842838.
#Sta/Elev= 30
  4621.8 2458.85  4642.2  2448.2  4647.8 2441.69  4652.9 2441.65  4699.8 2415.51
  4704.9 2415.26  4751.8 2392.21  4803.9 2370.65  4808.9  2370.7  4825.5 2360.85
  4947.6 2325.19    4965 2325.15  4994.7 2319.13    4995 2318.63  4998.7 2319.13
  5008.8 2319.72  5016.3 2324.32  5021.4 2322.69  5071.4    2326  5116.4 2343.04
  5166.5 2347.15  5216.5 2357.87  5261.5 2378.01  5266.6 2378.12  5311.6 2400.87
  5316.7    2401    5356 2420.22  5361.7 2425.12  5366.8 2425.01  5386.7 2435.73
#Mann= 3 ,-1 , 0
  4621.8     .16       0  4994.7     .07       0  4998.7     .16       0
Bank Sta=4994.7,4998.7
XS Rating Curve= 0 ,0
Exp/Cntr=0.3,0.1

Type RM Length L Ch R = 1 ,60500   ,373,373,373
BEGIN DESCRIPTION:
Stink Creek 113.0
END DESCRIPTION:
XS GIS Cut Line= 3
      1436305.04      6842988.02      1436648.33      6843179.75
      1437054.99        6843138.
#Sta/Elev= 30
  4606.8 2417.61  4614.7 2416.35  4620.5    2412  4636.5 2409.58  4642.2 2405.26
  4695.8 2386.99  4701.6 2380.56    4745 2361.68    4761  2355.7    4777 2353.06
  4826.1 2334.73  4847.8 2328.86  4907.2 2320.21  4923.2 2314.51  4938.9 2316.59
  4944.9 2313.64  4950.6  2314.7  4960.9  2309.8  4966.6 2311.95  4973.3 2304.25
  4980.6 2300.84  4980.8 2300.34  4984.6 2300.84    5000 2301.39  5026.8 2306.91
    5057 2307.24  5097.2 2312.51  5262.5 2343.69  5361.7 2379.78  5408.8  2400.9
#Mann= 3 ,-1 , 0
  4606.8     .16       0  4980.6     .07       0  4984.6     .16       0
Bank Sta=4980.6,4984.6
XS Rating Curve= 0 ,0
Exp/Cntr=0.3,0.1

Type RM Length L Ch R = 1 ,60127   ,296,296,296
BEGIN DESCRIPTION:
Stink Creek 4291
END DESCRIPTION:
XS GIS Cut Line= 3
      1436596.27      6843405.28      1436754.84      6843457.99
       1437046.5      6843282.29
#Sta/Elev= 30
  4832.9 2308.82  4894.8 2309.35  4915.7 2303.64    4921 2305.08  4926.4 2301.57
  4947.3 2297.95  4952.6 2299.25    4958 2295.62  4968.6 2291.12    4979 2292.25
  4982.3 2290.17  4982.5 2289.67  4986.3 2290.17  4997.5 2297.73    5003 2297.73
  5013.7 2300.06  5023.4 2300.39  5050.6 2305.13  5087.5 2312.94  5093.6 2315.04
  5124.4 2316.85  5167.1 2325.23    5204  2333.7  5210.3 2336.12  5233.7 2341.69
  5240.9 2345.32  5262.2 2350.87  5299.1 2365.76  5320.5  2372.7  5340.5 2382.14
#Mann= 3 ,-1 , 0
  4832.9     .16       0  4982.3     .07       0  4986.3     .16       0
Bank Sta=4982.3,4986.3
XS Rating Curve= 0 ,0
Exp/Cntr=0.3,0.1

Type RM Length L Ch R = 1 ,59831   ,331,331,331
BEGIN DESCRIPTION:
Stink Creek 112.0
END DESCRIPTION:
XS GIS Cut Line= 3
      1436509.28      6843337.59      1436618.15      6843674.22
      1436958.73      6843815.46
#Sta/Elev= 30
  4646.2 2311.63  4714.2 2308.53  4810.3 2300.15  4815.5  2301.4  4842.3 2299.72
  4847.5 2301.16  4874.3 2298.25  4879.6  2299.9  4906.3 2297.75  4911.6 2299.16
  4961.9 2290.39  4975.6 2285.32  4980.9 2280.49  4981.2 2279.99  4984.9 2280.49
  4993.5 2281.16  4999.4  2285.2  5023.3 2290.29  5047.2 2290.68  5052.6 2292.39
    5071 2293.36  5076.4 2295.95  5100.3 2294.11  5105.7 2296.91  5124.2  2295.8
  5129.6 2298.98  5148.1 2298.29  5206.7 2306.47  5336.9 2315.88  5368.7 2320.02
#Mann= 3 ,-1 , 0
  4646.2     .16       0  4980.9     .07       0  4984.9     .16       0
Bank Sta=4980.9,4984.9
XS Rating Curve= 0 ,0
Exp/Cntr=0.3,0.1

Type RM Length L Ch R = 1 ,59500   ,500,500,500
BEGIN DESCRIPTION:
Stink Creek 111.0
END DESCRIPTION:
XS GIS Cut Line= 3
      1436005.03      6843738.01      1436524.45      6843957.25
      1436904.98        6844038.
#Sta/Elev= 30
  4436.2 2424.22  4474.5 2404.19  4490.4 2399.36  4521.9 2384.33  4527.3 2384.08
  4533.9 2378.35    4551 2369.21  4566.4 2363.97  4574.7 2358.88  4580.2 2358.79
  4627.6 2339.85  4664.1 2328.53  4704.1 2317.76    4757 2307.87  4829.8 2302.74
  4910.1 2292.26    4963    2289  4968.4 2290.29  4978.9 2284.98  4986.7 2276.17
  4992.1 2279.46  4995.6 2273.24  4995.8 2272.74  4999.6 2273.24  5010.8 2273.57
  5026.9 2281.73    5270 2296.94  5329.6 2306.79  5364.2 2316.84    5389 2319.89
#Mann= 5 ,-1 , 0
  4436.2     .07       0  4829.8     .16       0  4995.6     .07       0
  4999.6     .16       0  5329.6     .07       0
Bank Sta=4995.6,4999.6
XS Rating Curve= 0 ,0
Exp/Cntr=0.3,0.1

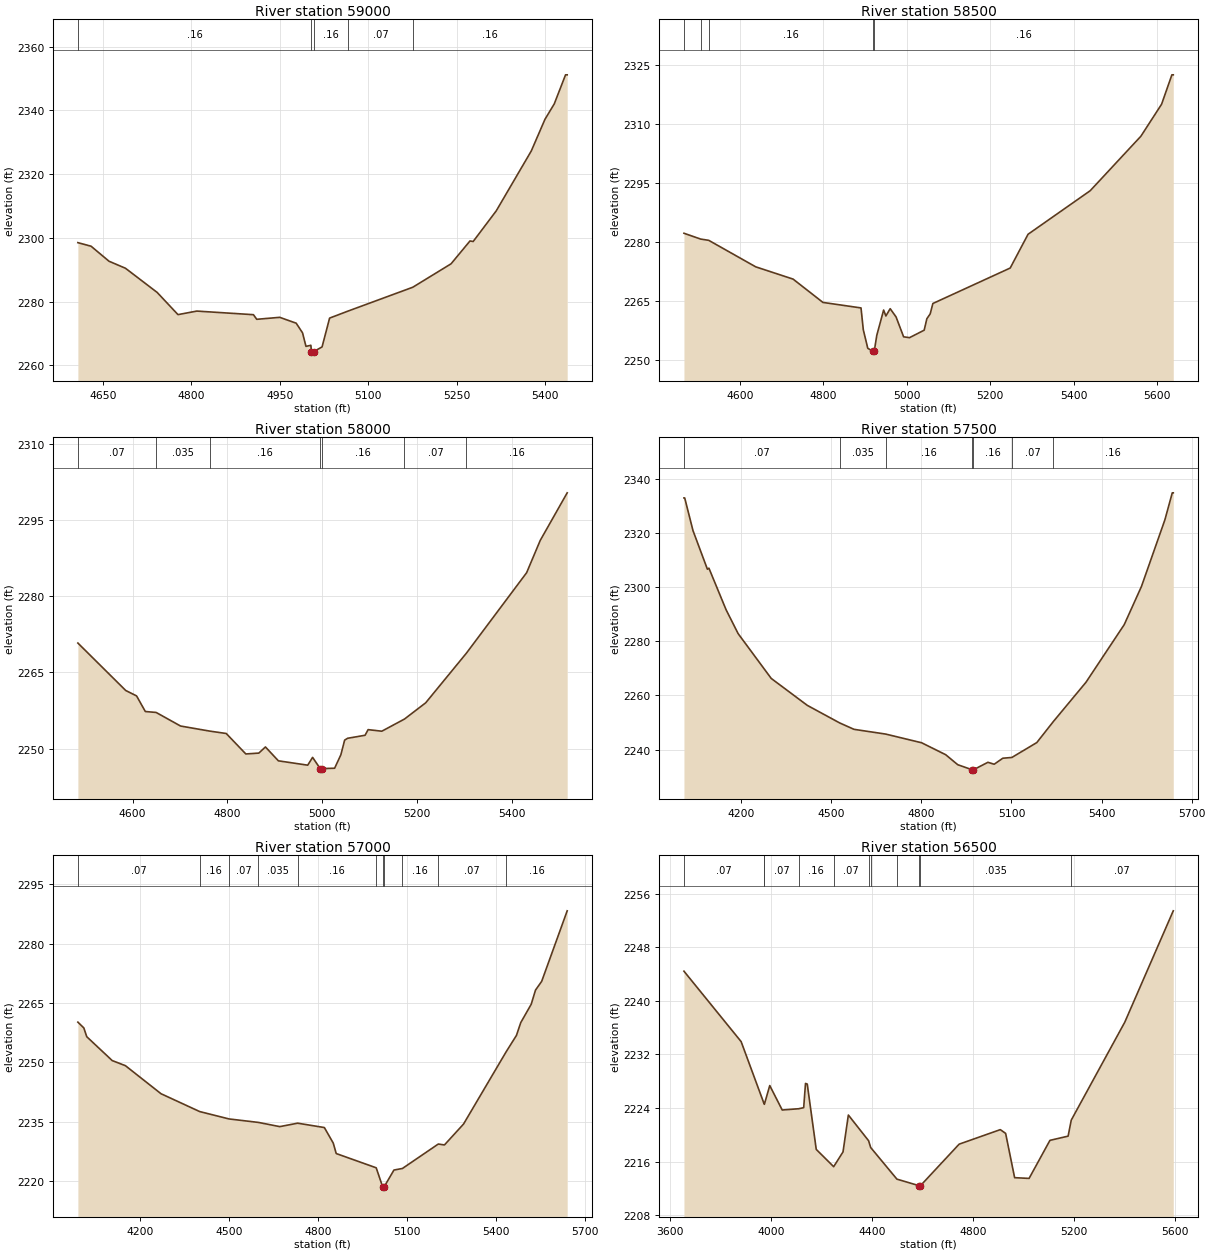
Type RM Length L Ch R = 1 ,59000   ,500,500,500
BEGIN DESCRIPTION:
Stink Creek 110.0
END DESCRIPTION:
XS GIS Cut Line= 3
      1436305.04      6844238.02      1436655.25      6844415.46
      1437055.03      6844237.99
#Sta/Elev= 30
  4607.4 2298.54  4629.8 2297.42  4660.2 2292.71  4688.1 2290.51  4741.9 2282.92
  4777.2 2275.96  4809.1 2277.07  4905.2 2275.94  4910.8 2274.49  4949.8 2275.11
  4977.7 2273.27  4988.5 2270.24  4994.3    2266  5002.6 2266.34  5003.6 2264.38
  5003.9 2263.88  5007.6 2264.38  5021.6 2265.83  5034.4 2274.87  5065.8 2277.08
  5175.5 2284.55  5240.4  2291.9  5272.5 2299.07  5277.9  2298.9    5317  2308.5
  5376.5 2327.31  5399.7 2337.24  5415.5 2342.09  5434.6 2351.19  5437.4 2351.19
#Mann= 5 ,-1 , 0
  4607.4     .16       0  5003.6     .07       0  5007.6     .16       0
  5065.8     .07       0  5175.5     .16       0
Bank Sta=5003.6,5007.6
XS Rating Curve= 0 ,0
Exp/Cntr=0.3,0.1

Type RM Length L Ch R = 1 ,58500   ,500,500,500
BEGIN DESCRIPTION:
Stink Creek 109.0
END DESCRIPTION:
XS GIS Cut Line= 3
      1436254.96      6844687.98      1436752.32       6844883.2
      1437155.02      6844387.97
#Sta/Elev= 30
  4465.7 2282.29  4505.8 2280.81  4525.1 2280.49  4637.6 2273.75  4727.3 2270.62
  4798.8 2264.69    4890 2263.29  4895.5 2257.73  4906.2 2253.03  4917.8 2252.29
  4918.1 2251.79  4921.8 2252.29  4927.7 2256.28  4944.2 2262.75  4949.6 2261.24
  4959.9  2263.1    4974    2261  4992.1 2255.94  5006.2 2255.72  5041.4 2257.63
  5047.8 2260.55  5055.8 2261.78  5062.2 2264.42  5247.5 2273.44  5290.3 2282.03
  5439.3 2293.12  5560.7 2306.98  5610.3 2315.12    5635  2322.6  5638.3  2322.6
#Mann= 5 ,-1 , 0
  4465.7     .16       0  4505.8     .07       0  4525.1     .16       0
  4917.8     .07       0  4921.8     .16       0
Bank Sta=4917.8,4921.8
XS Rating Curve= 0 ,0
Exp/Cntr=0.3,0.1

Type RM Length L Ch R = 1 ,58000   ,500,500,500
BEGIN DESCRIPTION:
Stink Creek 108.0
END DESCRIPTION:
XS GIS Cut Line= 3
      1436354.99        6845438.      1436854.97       6845313.7
      1437255.04      6844987.97
#Sta/Elev= 30
  4484.8 2270.78  4585.6 2261.44  4608.5 2260.37  4626.9  2257.3  4649.8 2257.11
  4701.2 2254.44  4762.7 2253.44  4797.4 2252.97  4838.7 2248.94  4866.1 2249.11
    4880 2250.32  4907.3 2247.59  4969.1 2246.73  4979.4 2248.27  4995.4 2246.06
  4995.7 2245.56  4999.4 2246.06  5025.8 2246.13    5039 2248.79  5046.9 2251.66
  5053.3 2252.03    5090 2252.62  5096.4 2253.73  5125.2 2253.42    5173 2255.81
  5217.8 2259.02  5303.7 2268.81  5430.4 2284.63  5459.1 2290.99  5515.9 2300.36
#Mann= 7 ,-1 , 0
  4484.8     .07       0  4649.8    .035       0  4762.7     .16       0
  4995.4     .07       0  4999.4     .16       0    5173     .07       0
  5303.7     .16       0
Bank Sta=4995.4,4999.4
XS Rating Curve= 0 ,0
Exp/Cntr=0.3,0.1

Type RM Length L Ch R = 1 ,57500   ,500,500,500
BEGIN DESCRIPTION:
Stink Creek 107.0
END DESCRIPTION:
XS GIS Cut Line= 3
      1436104.96        6845788.      1437093.77      6845726.83
        1437505.        6845238.
#Sta/Elev= 30
  4009.3 2333.02  4011.8 2333.02  4039.4 2320.94  4087.4 2306.66  4092.4 2307.07
  4149.6 2291.69  4189.7 2282.87  4299.9 2266.31  4420.1 2256.35  4527.9 2249.86
  4575.8 2247.49  4681.3 2245.74  4800.9 2242.53    4881 2238.11  4921.1 2234.42
  4969.2 2232.55  4969.4 2232.05  4973.2 2232.55  5021.6 2235.31  5042.5  2234.6
  5071.1 2236.82  5101.3  2237.1  5184.3  2242.6  5239.2 2250.34  5348.1 2264.89
  5475.6 2286.21  5532.8 2300.28  5610.8 2324.89  5635.5  2334.9  5638.8  2334.9
#Mann= 7 ,-1 , 0
  4009.3     .07       0  4527.9    .035       0  4681.3     .16       0
  4969.2     .07       0  4973.2     .16       0  5101.3     .07       0
  5239.2     .16       0
Bank Sta=4969.2,4973.2
XS Rating Curve= 0 ,0
Exp/Cntr=0.3,0.1

Type RM Length L Ch R = 1 ,57000   ,500,500,500
BEGIN DESCRIPTION:
Stink Creek 106.0
END DESCRIPTION:
XS GIS Cut Line= 3
        1436355.        6846138.      1437362.77      6846094.64
      1437754.98      6845588.02
#Sta/Elev= 30
  3991.3 2260.16  4011.3  2258.7  4021.3 2256.47    4107 2250.45  4151.5 2249.16
  4271.6 2242.07  4401.7 2237.57  4500.9  2235.7  4600.1 2234.82  4671.9 2233.76
  4732.1 2234.63  4822.1 2233.53  4852.1  2229.6  4862.1 2226.96  4996.9 2223.36
    5019 2218.47  5019.3 2217.97    5023 2218.47  5056.7 2222.79  5085.3 2223.19
  5206.2 2229.36  5226.9 2229.13  5291.2  2234.4  5434.7 2252.64  5469.6  2256.8
  5484.1 2260.03  5519.4 2264.68  5533.9 2268.26  5554.7 2270.46  5640.7 2288.28
#Mann= 11 ,-1 , 0
  3991.3     .07       0  4401.7     .16       0  4500.9     .07       0
  4600.1    .035       0  4732.1     .16       0  4996.9     .07       0
    5019     .07       0    5023     .07       0  5085.3     .16       0
  5206.2     .07       0  5434.7     .16       0
Bank Sta=5019,5023
XS Rating Curve= 0 ,0
Exp/Cntr=0.3,0.1

Type RM Length L Ch R = 1 ,56500   ,500,500,500
BEGIN DESCRIPTION:
Stink Creek 105.0
END DESCRIPTION:
XS GIS Cut Line= 3
        1436705.        6847288.      1437680.14      6846362.95
      1437955.02      6845837.96
#Sta/Elev= 30
  3655.9 2244.42  3882.2 2233.91    3972 2224.74  3974.2 2224.55  3995.5 2227.35
  4044.8  2223.7  4110.3 2223.89  4129.8 2224.05    4137 2227.67  4143.9 2227.57
  4179.5 2217.82  4248.5 2215.24  4285.5 2217.45  4306.6 2222.95  4386.8 2219.11
    4395  2218.1  4498.8 2213.38  4587.7 2212.39  4587.9 2211.89  4591.7 2212.39
    4745  2218.6    4908 2220.77  4929.1 2220.21  4964.7  2213.6  5021.9 2213.49
  5104.5 2219.17  5176.4  2219.8  5188.8 2222.19  5400.7 2236.81  5592.6 2253.43
#Mann= 11 ,-1 , 0
  3655.9     .07       0    3972     .16       0  3974.2     .07       0
  4110.3     .16       0  4248.5     .07       0  4386.8     .16       0
    4395     .07       0  4498.8    .035       0  4587.7    .035       0
  4591.7    .035       0  5188.8     .07       0
Bank Sta=4587.7,4591.7
XS Rating Curve= 0 ,0
Exp/Cntr=0.3,0.1

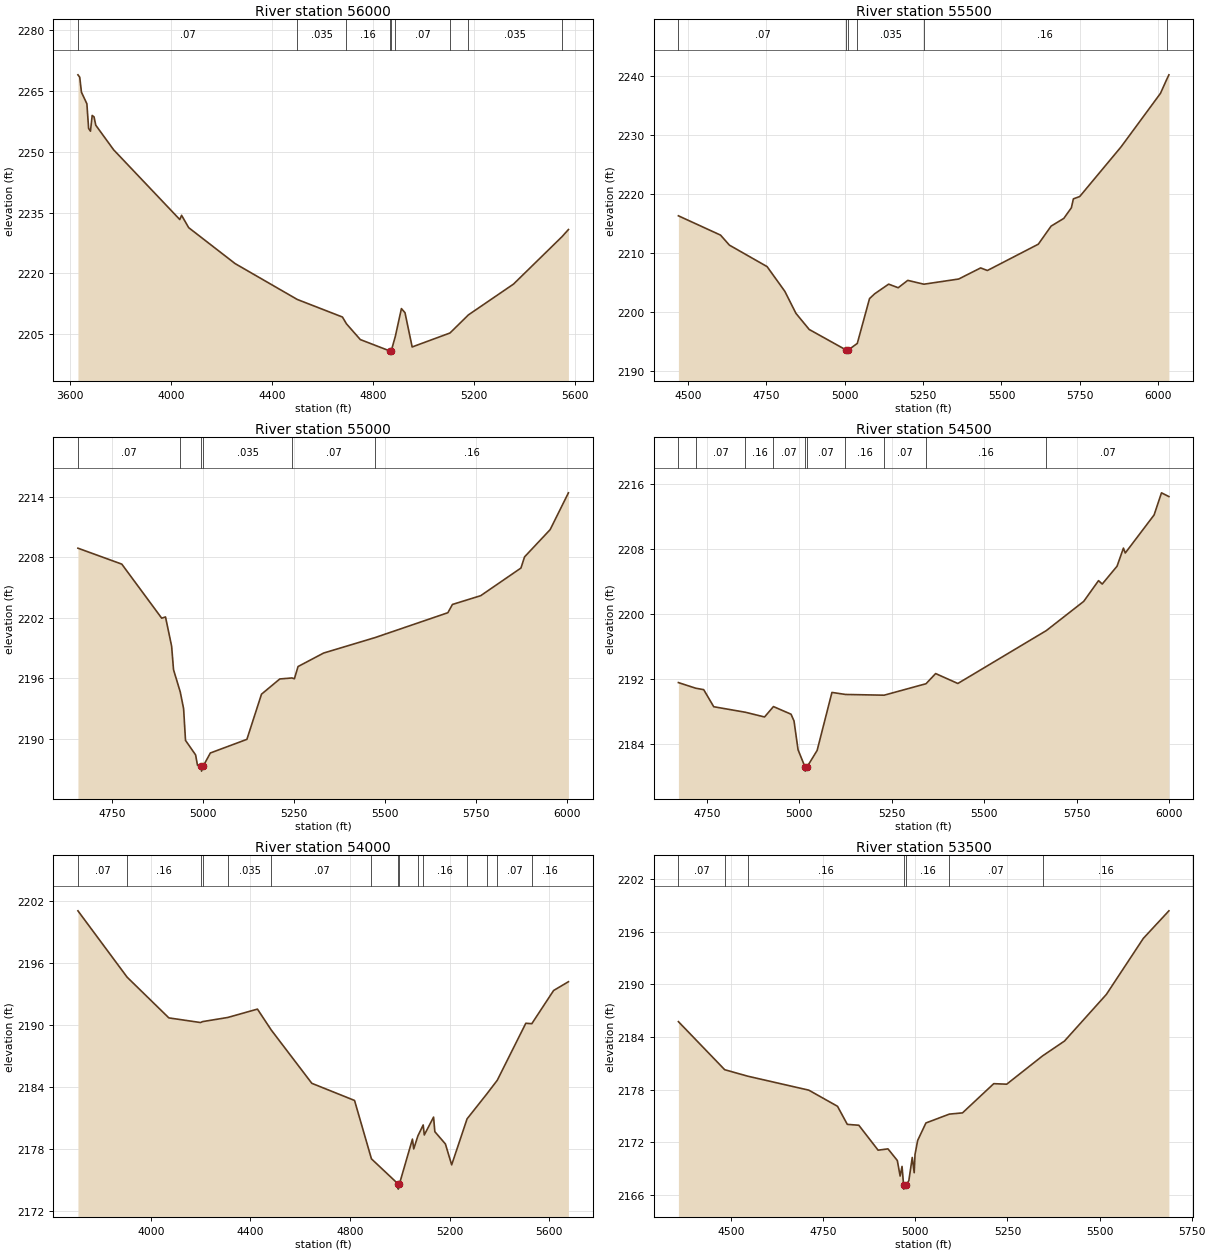
Type RM Length L Ch R = 1 ,56000   ,500,500,500
BEGIN DESCRIPTION:
Stink Creek 104.0
END DESCRIPTION:
XS GIS Cut Line= 3
        1436955.        6847638.      1437954.81      6846705.18
      1438204.99      6846188.01
#Sta/Elev= 30
  3632.6 2268.96  3639.7 2268.38  3646.5 2264.68    3668 2261.82  3674.9 2255.73
  3682.2 2255.07    3689 2258.94  3696.4 2258.59  3703.2 2256.54    3774 2250.47
  4035.9 2233.28  4042.9 2234.33  4071.1 2231.28  4255.2 2222.41    4501 2213.58
  4679.8 2209.25  4695.8 2207.57  4750.6 2203.69  4868.8 2200.85    4869 2200.35
  4872.8 2200.85  4889.3 2204.51  4913.3 2211.33  4927.5 2210.31  4955.8 2201.87
  5105.5 2205.31  5178.6 2209.78  5357.1 2217.37  5548.8 2229.04  5574.5 2230.81
#Mann= 9 ,-1 , 0
  3632.6     .07       0    4501    .035       0  4695.8     .16       0
  4868.8     .07       0  4872.8     .16       0  4889.3     .07       0
  5105.5     .16       0  5178.6    .035       0  5548.8     .16       0
Bank Sta=4868.8,4872.8
XS Rating Curve= 0 ,0
Exp/Cntr=0.3,0.1

Type RM Length L Ch R = 1 ,55500   ,500,500,500
BEGIN DESCRIPTION:
Stink Creek 103.0
END DESCRIPTION:
XS GIS Cut Line= 3
      1437854.99      6847488.01      1438222.94      6847105.99
      1438404.99      6846088.04
#Sta/Elev= 30
  4469.6 2216.25    4604 2212.98  4632.3 2211.28  4752.5 2207.64  4809.1 2203.45
  4844.5 2199.72  4886.8 2196.99  5005.6 2193.48    5006 2192.98  5010.7 2193.48
  5040.2 2194.63  5079.2 2202.22  5095.7 2203.04  5140.2 2204.67  5170.7 2204.06
  5201.1 2205.31  5252.6 2204.66  5363.7 2205.54  5433.7 2207.42  5455.1 2206.98
  5617.6 2211.44  5658.3  2214.5  5698.9 2215.81    5723 2217.61  5729.4 2219.12
  5749.7 2219.52  5881.8 2227.95  6007.2    2237    6027 2239.34  6034.1 2240.14
#Mann= 6 ,-1 , 0
  4469.6     .07       0  5005.6     .07       0  5010.7     .07       0
  5040.2    .035       0  5252.6     .16       0    6027     .07       0
Bank Sta=5005.6,5010.7
XS Rating Curve= 0 ,0
Exp/Cntr=0.3,0.1

Type RM Length L Ch R = 1 ,55000   ,500,500,500
BEGIN DESCRIPTION:
Stink Creek 102.0
END DESCRIPTION:
XS GIS Cut Line= 3
        1438205.        6847538.      1438533.22      6847438.42
        1438455.      6846437.97
#Sta/Elev= 30
    4657 2208.91  4777.4 2207.33  4886.9 2201.97  4897.4 2202.09  4914.2 2199.19
  4919.4 2196.86  4937.9 2194.65  4947.1 2192.99  4952.3 2189.85    4980 2188.41
  4985.2 2187.39  4995.8  2187.3  4996.2  2186.8  5000.9  2187.3  5020.5  2188.6
  5120.8 2189.95  5160.9 2194.43  5211.1 2195.94  5244.6 2196.04  5251.2 2195.96
  5261.2 2197.17  5331.4 2198.51  5473.2 2200.05  5672.5 2202.51  5685.1 2203.33
  5762.7  2204.2  5873.1 2206.94  5883.1 2208.05  5953.3 2210.75  6003.5  2214.4
#Mann= 6 ,-1 , 0
    4657     .07       0  4937.9    .035       0  4995.8    .035       0
  5000.9    .035       0  5244.6     .07       0  5473.2     .16       0
Bank Sta=4995.8,5000.9
XS Rating Curve= 0 ,0
Exp/Cntr=0.3,0.1

Type RM Length L Ch R = 1 ,54500   ,500,500,500
BEGIN DESCRIPTION:
Stink Creek 101.0
END DESCRIPTION:
XS GIS Cut Line= 3
      1438778.44      6847705.37      1438963.57      6847436.43
        1439005.      6846437.99
#Sta/Elev= 30
  4673.5 2191.52  4720.2 2190.83  4741.9 2190.65    4769 2188.55  4854.7 2187.87
  4906.3 2187.29  4930.4 2188.57    4978 2187.63    4986  2186.8  4996.9 2183.26
  5015.8 2181.13  5016.2 2180.63    5021 2181.13  5048.5 2183.18  5088.5 2190.31
  5125.1 2190.06  5229.6 2189.97  5342.8 2191.38  5368.8 2192.63  5428.8 2191.41
  5668.1 2197.92  5769.1 2201.51  5809.1 2204.06  5819.1 2203.64  5859.2 2205.84
  5876.4 2208.06  5881.4 2207.46  5959.3 2212.14  5979.3 2214.86  5999.3  2214.4
#Mann= 10 ,-1 , 0
  4673.5    .035       0  4720.2     .07       0  4854.7     .16       0
  4930.4     .07       0  5015.8     .07       0    5021     .07       0
  5125.1     .16       0  5229.6     .07       0  5342.8     .16       0
  5668.1     .07       0
Bank Sta=5015.8,5021
XS Rating Curve= 0 ,0
Exp/Cntr=0.3,0.1

Type RM Length L Ch R = 1 ,54000   ,500,500,500
BEGIN DESCRIPTION:
Stink Creek 100.0
END DESCRIPTION:
XS GIS Cut Line= 3
      1438105.02        6847888.      1439378.02      6847660.91
      1439532.74      6847001.31
#Sta/Elev= 30
  3706.9 2201.04  3904.5 2194.62  4072.2 2190.68  4199.3 2190.23  4207.7 2190.32
  4308.7 2190.72  4428.1 2191.53  4483.5 2189.51  4646.5 2184.35  4818.2 2182.69
  4886.1 2177.04  4993.3 2174.61  4993.7 2174.11  4998.5 2174.61  5050.8 2178.95
    5056    2178  5072.7 2179.26    5094 2180.32  5098.4 2179.35  5135.7 2181.08
  5140.8 2179.67  5183.3 2178.48  5208.4 2176.46  5270.3 2180.91  5348.6 2183.29
  5391.5 2184.64  5506.3 2190.16  5530.4 2190.12  5617.9 2193.33  5677.5 2194.18
#Mann= 15 ,-1 , 0
  3706.9     .07       0  3904.5     .16       0  4199.3     .07       0
  4207.7     .16       0  4308.7    .035       0  4483.5     .07       0
  4886.1     .16       0  4993.3     .07       0  4998.5     .16       0
  5072.7     .07       0    5094     .16       0  5270.3     .07       0
  5348.6     .16       0  5391.5     .07       0  5530.4     .16       0
Bank Sta=4993.3,4998.5
XS Rating Curve= 0 ,0
Exp/Cntr=0.3,0.1

Type RM Length L Ch R = 1 ,53500   ,348,348,348
BEGIN DESCRIPTION:
Stink Creek 99.0
END DESCRIPTION:
XS GIS Cut Line= 3
      1439016.13      6847878.13       1439631.9       6848064.3
      1440169.19      6847634.25
#Sta/Elev= 30
  4356.7 2185.75  4482.4 2180.27  4545.2 2179.53  4710.7 2177.94  4788.6  2176.1
  4815.2 2174.04  4846.5 2173.94  4898.8  2171.1  4925.6 2171.25    4951 2169.92
  4958.6 2168.15  4963.8 2169.25  4967.9 2167.16  4968.4 2166.66  4975.8 2167.16
  4982.3 2167.64  4991.5 2170.27  4996.8 2168.53    4999 2170.61  5006.2 2172.21
  5028.6  2174.2  5092.2 2175.21  5127.9 2175.35  5212.7 2178.68  5247.9 2178.62
  5345.1 2181.84  5404.8 2183.54  5518.4 2188.85  5618.8 2195.24  5688.2 2198.38
#Mann= 7 ,-1 , 0
  4356.7     .07       0  4482.4    .035       0  4545.2     .16       0
  4967.9     .07       0  4975.8     .16       0  5092.2     .07       0
  5345.1     .16       0
Bank Sta=4967.9,4975.8
XS Rating Curve= 0 ,0
Exp/Cntr=0.3,0.1

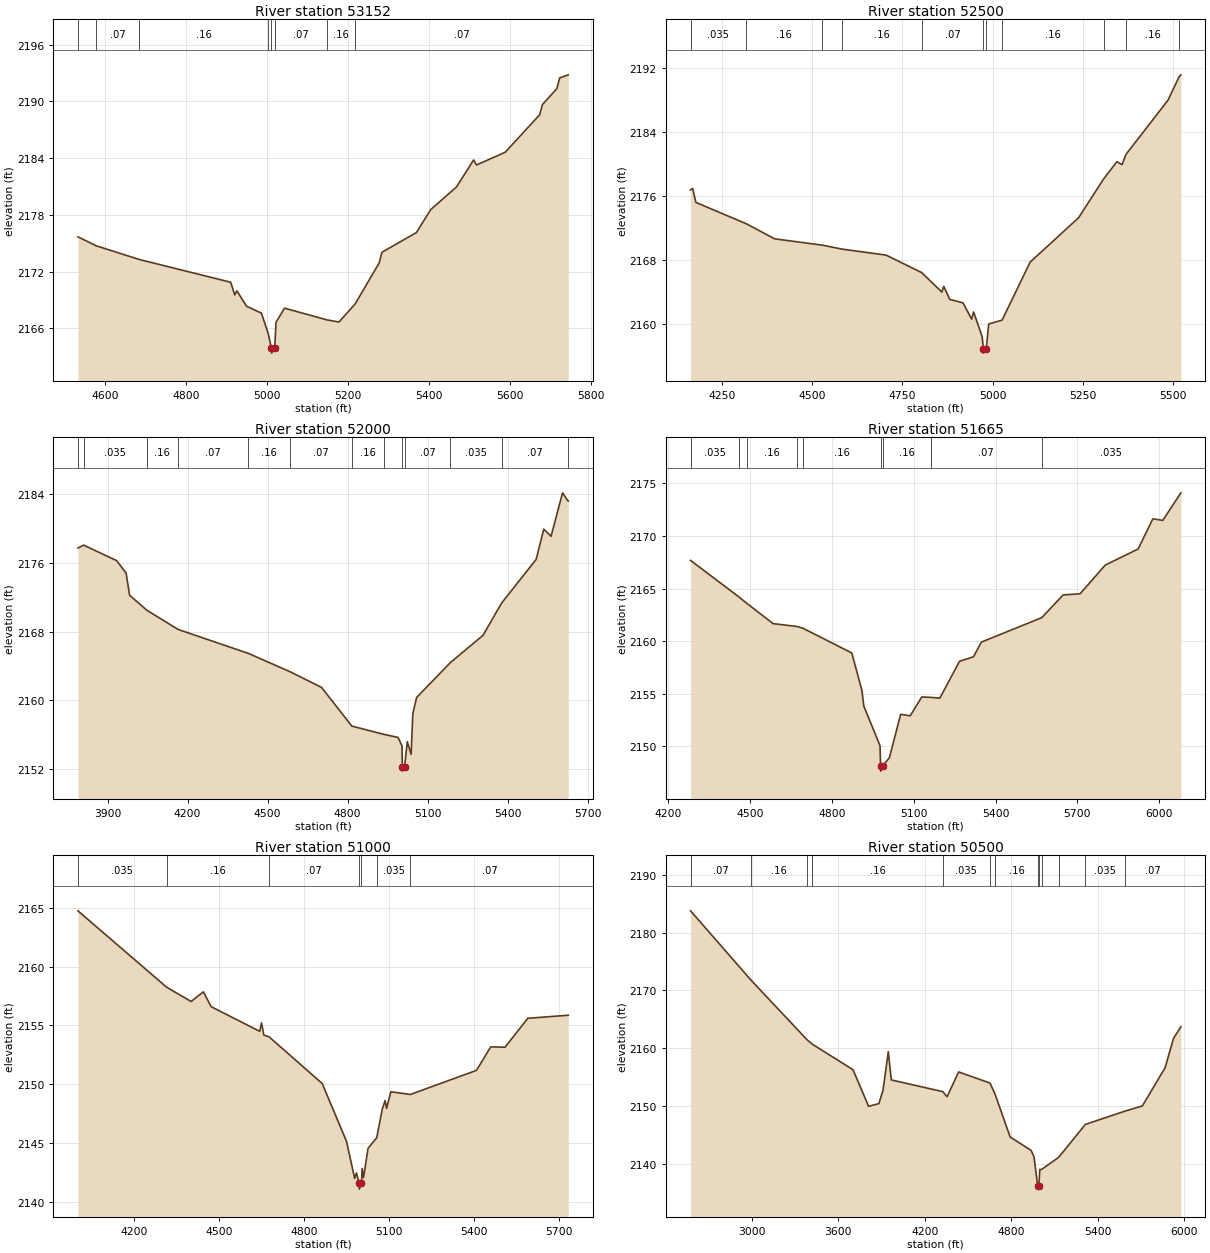
Type RM Length L Ch R = 1 ,53152   ,652,652,652
BEGIN DESCRIPTION:
Stink Creek 98.0
END DESCRIPTION:
XS GIS Cut Line= 3
      1439236.17       6848224.3      1439668.22      6848401.81
      1440205.03      6847887.97
#Sta/Elev= 30
  4532.9 2175.68  4578.5 2174.72  4684.3 2173.28    4910 2170.87  4919.8 2169.53
  4925.2 2169.96  4949.2 2168.33  4985.7  2167.6  5002.2  2165.5  5010.6 2163.87
  5011.1 2163.37  5018.5 2163.87  5021.8 2166.64  5042.8 2168.13  5147.2 2166.89
  5177.1 2166.66  5217.2 2168.58  5276.2  2172.9  5283.4 2174.05  5368.3 2176.13
  5403.6 2178.56  5467.1 2180.95  5509.5 2183.81  5516.8 2183.28  5587.5 2184.63
  5672.4 2188.59  5679.4 2189.68  5714.9 2191.36  5721.8 2192.49  5743.1 2192.82
#Mann= 8 ,-1 , 0
  4532.9    .035       0  4578.5     .07       0  4684.3     .16       0
  5002.2     .07       0  5010.6     .07       0  5018.5     .07       0
  5147.2     .16       0  5217.2     .07       0
Bank Sta=5010.6,5018.5
XS Rating Curve= 0 ,0
Exp/Cntr=0.3,0.1

Type RM Length L Ch R = 1 ,52500   ,500,500,500
BEGIN DESCRIPTION:
Stink Creek 97.0
END DESCRIPTION:
XS GIS Cut Line= 3
      1439229.58      6848356.04      1440004.93      6848674.48
      1440405.03      6848337.97
#Sta/Elev= 30
  4161.8 2176.74  4167.7 2176.92  4176.6 2175.18  4316.2 2172.53  4395.4 2170.64
  4527.8 2169.85  4580.9 2169.37  4704.7 2168.61  4803.3 2166.43  4859.3 2164.01
  4864.7 2164.71  4881.2 2163.09  4918.1 2162.66    4942 2160.63  4947.4 2161.53
  4971.4 2158.42  4974.5 2156.89    4975 2156.39  4982.5 2156.89  4989.3 2160.02
  5026.6 2160.51  5104.6 2167.75  5238.6 2173.26  5308.1 2178.09  5345.2 2180.26
  5359.5 2179.89  5370.7 2181.19    5487 2187.93    5518 2190.86  5522.8 2191.09
#Mann= 11 ,-1 , 0
  4161.8    .035       0  4316.2     .16       0  4527.8     .07       0
  4580.9     .16       0  4803.3     .07       0  4974.5     .07       0
  4982.5     .07       0  5026.6     .16       0  5308.1     .07       0
  5370.7     .16       0    5518     .07       0
Bank Sta=4974.5,4982.5
XS Rating Curve= 0 ,0
Exp/Cntr=0.3,0.1

Type RM Length L Ch R = 1 ,52000   ,335,335,335
BEGIN DESCRIPTION:
Stink Creek 96.0
END DESCRIPTION:
XS GIS Cut Line= 3
        1439155.        6848438.      1440154.81      6849121.66
      1440555.03      6848637.97
#Sta/Elev= 30
  3788.8 2177.71  3810.2 2178.05  3933.8 2176.25  3969.6 2174.79  3982.6 2172.22
  4046.4  2170.5    4164 2168.25  4427.9 2165.46  4584.2 2163.33  4702.3 2161.51
    4816 2157.01  4936.8 2156.04  4989.4 2155.69  5004.1  2154.7  5005.6 2152.27
  5006.1 2151.77  5013.7 2152.27    5024 2155.19  5038.4 2153.73  5044.8 2158.45
  5059.2 2160.34  5185.9  2164.4    5308 2167.56  5377.9 2171.32  5507.3 2176.39
  5535.9 2179.91  5563.3 2179.08  5606.3 2184.13  5626.5 2183.19  5627.8 2183.19
#Mann= 13 ,-1 , 0
  3788.8     .07       0  3810.2    .035       0  4046.4     .16       0
    4164     .07       0  4427.9     .16       0  4584.2     .07       0
    4816     .16       0  4936.8     .07       0  5005.6     .07       0
  5013.7     .07       0  5185.9    .035       0  5377.9     .07       0
  5626.5     .16       0
Bank Sta=5005.6,5013.7
XS Rating Curve= 0 ,0
Exp/Cntr=0.3,0.1

Type RM Length L Ch R = 1 ,51665   ,665,665,665
BEGIN DESCRIPTION:
Stink Creek 95.0
END DESCRIPTION:
XS GIS Cut Line= 3
      1439304.96      6848887.98      1439903.97      6849282.58
      1440954.99        6849038.
#Sta/Elev= 30
  4282.7 2167.68  4458.8 2164.23  4488.1 2163.61  4585.4 2161.67  4673.9 2161.39
  4695.2 2161.22  4873.5 2158.88  4910.7  2155.3  4917.4 2153.84  4976.9 2150.06
  4978.9 2148.15  4979.4 2147.65    4987 2148.15  5011.3 2148.93  5052.4 2153.05
  5087.4 2152.91    5130  2154.7  5161.8 2154.66  5196.1 2154.59    5268 2158.09
  5319.3 2158.52  5348.1 2159.91  5569.6 2162.24  5647.9  2164.4  5709.5  2164.5
  5801.9 2167.23  5922.3 2168.76  5976.4 2171.63  6012.7 2171.48  6079.1  2174.1
#Mann= 9 ,-1 , 0
  4282.7    .035       0  4458.8     .07       0  4488.1     .16       0
  4673.9     .07       0  4695.2     .16       0  4978.9     .07       0
    4987     .16       0  5161.8     .07       0  5569.6    .035       0
Bank Sta=4978.9,4987
XS Rating Curve= 0 ,0
Exp/Cntr=0.3,0.1

Type RM Length L Ch R = 1 ,51000   ,500,500,500
BEGIN DESCRIPTION:
Stink Creek 94.0
END DESCRIPTION:
XS GIS Cut Line= 3
      1439352.28      6849039.69      1439968.65      6849824.22
      1440696.75      6849734.63
#Sta/Elev= 30
  4002.3 2164.75  4315.2 2158.26    4402 2157.04  4445.3 2157.86  4472.5  2156.6
  4644.2  2154.5  4650.6 2155.22  4658.7 2154.18  4676.8 2154.04  4864.9 2150.06
  4950.6 2145.14  4979.4 2141.99  4985.9 2142.46  4995.2 2141.58  4995.7 2141.08
  5003.3 2141.58  5005.7 2142.84  5010.7 2142.06  5026.6 2144.55  5057.2 2145.45
  5076.9 2147.89  5086.9 2148.61    5092 2147.95  5107.2 2149.36    5176 2149.13
  5409.4 2151.18  5459.8 2153.18  5510.2 2153.15  5590.8 2155.61  5733.6 2155.87
#Mann= 7 ,-1 , 0
  4002.3    .035       0  4315.2     .16       0  4676.8     .07       0
  4995.2     .07       0  5003.3     .07       0  5057.2    .035       0
    5176     .07       0
Bank Sta=4995.2,5003.3
XS Rating Curve= 0 ,0
Exp/Cntr=0.3,0.1

Type RM Length L Ch R = 1 ,50500   ,500,500,500
BEGIN DESCRIPTION:
Stink Creek 93.0
END DESCRIPTION:
XS GIS Cut Line= 3
      1438404.97      6848287.96      1439804.67      6850268.23
      1440754.99        6850488.
#Sta/Elev= 30
    2575 2183.76  2993.1  2171.8  3383.1 2161.44  3419.3 2160.68  3701.7 2156.26
  3809.8 2149.93  3881.2 2150.39  3909.8 2152.72  3946.4 2159.38  3967.3 2154.49
  4324.4 2152.46  4353.8 2151.58  4433.9 2155.87  4651.6 2153.95  4686.8 2152.03
  4791.5 2144.61  4936.1 2142.31  4957.1 2141.16  4982.5 2136.09    4983 2135.59
  4990.8 2136.09  4996.8 2138.98  5010.1 2139.01  5127.5 2141.09  5312.8 2146.79
  5587.8 2149.09  5708.6    2150    5866 2156.61  5924.1 2161.67  5975.4  2163.7
#Mann= 13 ,-1 , 0
    2575     .07       0  2993.1     .16       0  3383.1     .07       0
  3419.3     .16       0  4324.4    .035       0  4651.6     .07       0
  4686.8     .16       0  4982.5     .07       0  4990.8     .16       0
  5010.1    .035       0  5127.5     .07       0  5312.8    .035       0
  5587.8     .07       0
Bank Sta=4982.5,4990.8
XS Rating Curve= 0 ,0
Exp/Cntr=0.3,0.1

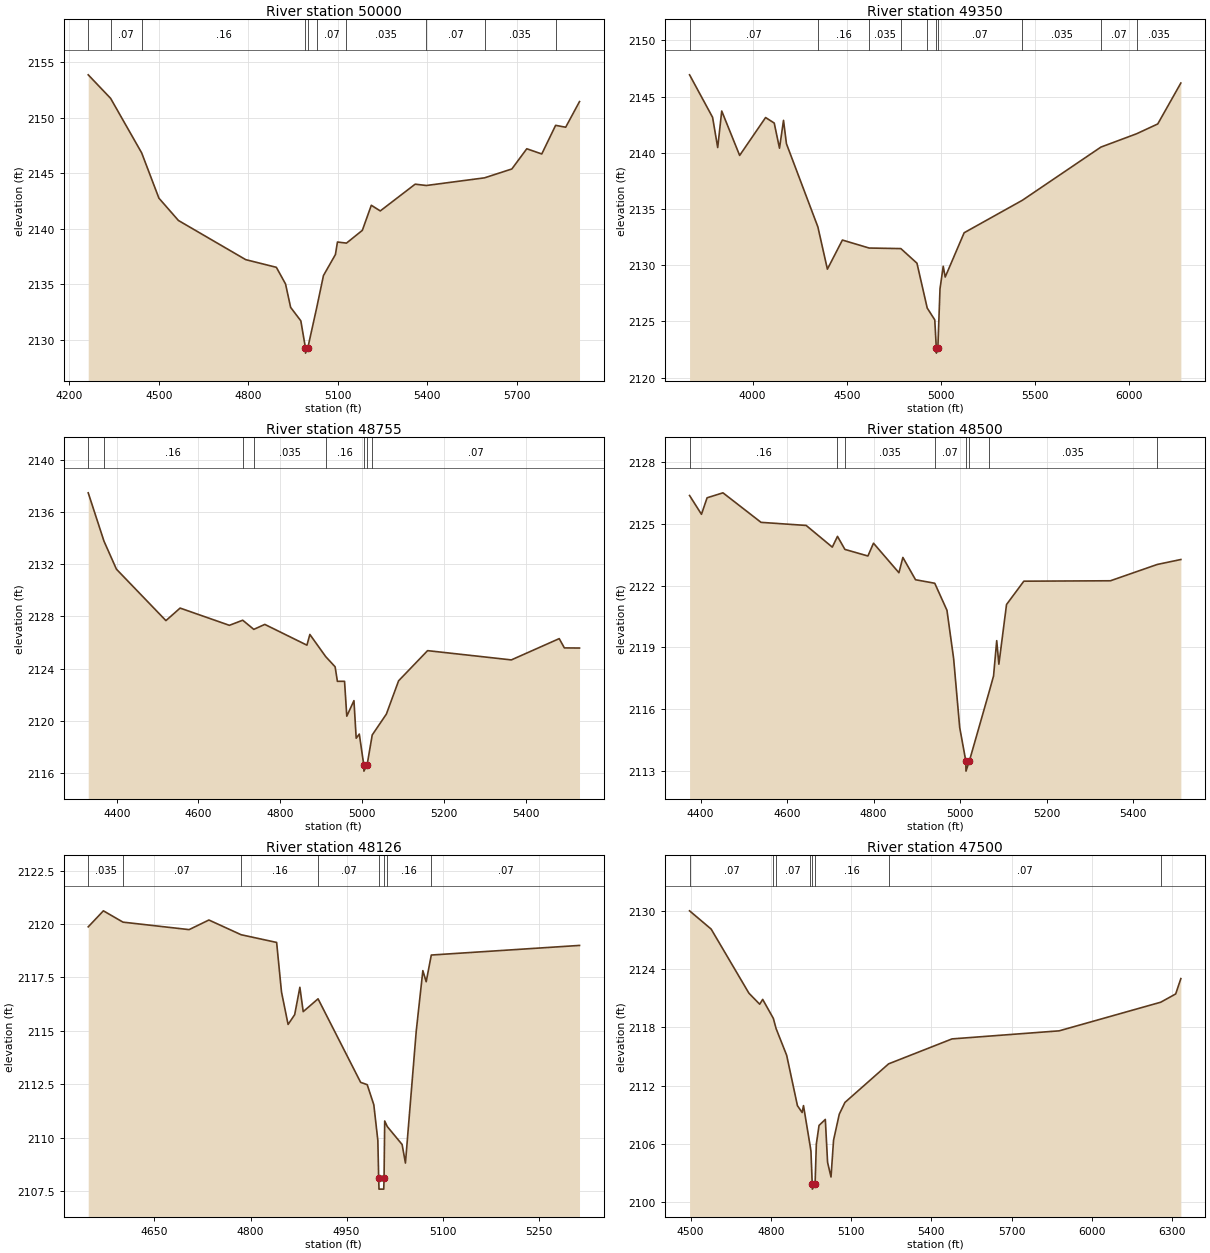
Type RM Length L Ch R = 1 ,50000   ,650,650,650
BEGIN DESCRIPTION:
Stink Creek 92.0
END DESCRIPTION:
XS GIS Cut Line= 3
      1439506.04      6850003.36      1439672.66      6850720.76
      1440581.27      6850650.83
#Sta/Elev= 30
  4263.5 2153.87  4338.6 2151.75  4442.7 2146.84  4500.6 2142.76    4566 2140.75
  4791.8 2137.22  4894.5 2136.53  4925.3 2135.03  4942.4 2132.92  4976.6 2131.71
  4991.9  2129.3  4992.4  2128.8  5000.2  2129.3  5030.2 2132.94  5052.5 2135.79
  5092.6 2137.68  5099.4 2138.81  5129.7 2138.71  5182.9 2139.86    5213 2142.12
  5243.1 2141.61  5360.1 2144.02  5397.6  2143.9  5592.7 2144.59  5684.4 2145.39
  5734.5 2147.21  5784.7 2146.74  5831.2 2149.32  5864.9 2149.15  5911.3 2151.46
#Mann= 10 ,-1 , 0
  4263.5    .035       0  4338.6     .07       0  4442.7     .16       0
  4991.9     .07       0  5000.2     .16       0  5030.2     .07       0
  5129.7    .035       0  5397.6     .07       0  5592.7    .035       0
  5831.2     .07       0
Bank Sta=4991.9,5000.2
XS Rating Curve= 0 ,0
Exp/Cntr=0.3,0.1

Type RM Length L Ch R = 1 ,49350   ,595,595,595
BEGIN DESCRIPTION:
Stink Creek 91.0
END DESCRIPTION:
XS GIS Cut Line= 3
      1438160.06      6850437.07      1439303.04      6851126.28
      1440555.59      6850894.05
#Sta/Elev= 30
  3665.3 2146.94  3787.5 2143.16  3814.7 2140.47  3836.1 2143.72  3931.2 2139.77
    4069 2143.14  4114.8 2142.65  4142.8 2140.41  4164.1 2142.89  4179.7 2140.81
  4346.6 2133.41  4397.1 2129.65  4476.8 2132.24  4618.8 2131.53  4787.2 2131.48
  4872.7 2130.18  4927.2 2126.19  4967.3 2125.14  4975.3 2122.68  4975.8 2122.18
  4983.7 2122.68  4995.1 2127.91  5012.2 2129.91  5022.7 2128.95  5123.3 2132.89
  5432.5 2135.78  5849.4 2140.51  6039.5  2141.7  6151.3 2142.57  6273.9 2146.21
#Mann= 10 ,-1 , 0
  3665.3     .07       0  4346.6     .16       0  4618.8    .035       0
  4787.2     .16       0  4927.2     .07       0  4975.3     .07       0
  4983.7     .07       0  5432.5    .035       0  5849.4     .07       0
  6039.5    .035       0
Bank Sta=4975.3,4983.7
XS Rating Curve= 0 ,0
Exp/Cntr=0.3,0.1

Type RM Length L Ch R = 1 ,48755   ,255,255,255
BEGIN DESCRIPTION:
Stink Creek 90.0
END DESCRIPTION:
XS GIS Cut Line= 3
        1438618.      6850885.27      1438896.84      6851494.05
      1439421.54      6851580.64
#Sta/Elev= 30
  4330.4 2137.46  4368.9 2133.76  4399.4 2131.61  4520.4 2127.67  4555.1 2128.63
  4675.6 2127.31  4708.2  2127.7  4735.3    2127  4762.2 2127.38  4865.2 2125.79
  4872.4 2126.61  4911.2 2124.91  4934.2 2124.13  4939.7 2123.02  4957.2 2123.02
  4962.7 2120.35  4980.2 2121.54  4985.7 2118.66  4993.3 2118.98  5004.1 2116.64
  5004.6 2116.14  5012.5 2116.64  5024.9 2118.91  5059.5 2120.51  5089.4 2123.06
  5160.3 2125.37  5365.1 2124.66  5482.2 2126.29  5494.8 2125.58  5531.8 2125.57
#Mann= 8 ,-1 , 0
  4330.4     .07       0  4368.9     .16       0  4708.2     .07       0
  4735.3    .035       0  4911.2     .16       0  5004.1     .07       0
  5012.5     .16       0  5024.9     .07       0
Bank Sta=5004.1,5012.5
XS Rating Curve= 0 ,0
Exp/Cntr=0.3,0.1

Type RM Length L Ch R = 1 ,48500   ,374,374,374
BEGIN DESCRIPTION:
Stink Creek 89.0
END DESCRIPTION:
XS GIS Cut Line= 3
      1438425.28      6851122.23      1438717.81        6851675.
      1439227.77      6851663.27
#Sta/Elev= 30
  4374.6 2126.36  4402.1 2125.45  4415.1 2126.25  4451.8 2126.49  4539.8 2125.06
  4644.1 2124.91  4704.5 2123.86  4716.5 2124.38  4733.6 2123.75  4786.8 2123.43
  4799.7 2124.05  4858.5 2122.62  4867.6 2123.36  4896.9 2122.28  4941.3 2122.11
  4969.5  2120.8  4984.9 2118.47  4998.9 2115.13    5013 2113.51  5013.5 2113.01
  5021.4 2113.51  5066.7 2116.83  5077.2 2117.62  5084.5 2119.33  5089.5 2118.19
  5107.2 2121.08  5147.2 2122.21  5347.3 2122.23  5455.5 2123.02  5510.1 2123.26
#Mann= 8 ,-1 , 0
  4374.6     .16       0  4716.5     .07       0  4733.6    .035       0
  4941.3     .07       0    5013     .07       0  5021.4     .07       0
  5066.7    .035       0  5455.5     .07       0
Bank Sta=5013,5021.4
XS Rating Curve= 0 ,0
Exp/Cntr=0.3,0.1

Type RM Length L Ch R = 1 ,48126   ,626,626,626
BEGIN DESCRIPTION:
Stink Creek 88.0
END DESCRIPTION:
XS GIS Cut Line= 3
      1438479.98      6851564.96      1438588.76      6852005.22
      1438888.26      6851911.24
#Sta/Elev= 30
  4546.5 2119.87  4570.2 2120.62  4600.8 2120.09  4704.1 2119.74    4735 2120.19
  4785.4  2119.5  4840.8 2119.14  4848.4 2116.82  4858.7  2115.3    4869 2115.76
  4877.1 2117.04  4882.3  2115.9  4905.5  2116.5    4972 2112.59  4982.3 2112.48
  4992.6 2111.54  4998.9 2109.87  5000.2 2108.09  5000.7 2107.59  5008.1 2107.59
  5008.6 2108.09  5009.6 2110.78  5013.6 2110.52  5036.8 2109.68    5042 2108.81
  5058.9    2115  5069.2 2117.82  5074.4  2117.3  5082.4 2118.55  5313.9    2119
#Mann= 8 ,-1 , 0
  4546.5    .035       0  4600.8     .07       0  4785.4     .16       0
  4905.5     .07       0  5000.2     .07       0  5008.6     .07       0
  5013.6     .16       0  5082.4     .07       0
Bank Sta=5000.2,5008.6
XS Rating Curve= 0 ,0
Exp/Cntr=0.3,0.1

Type RM Length L Ch R = 1 ,47500   ,500,500,500
BEGIN DESCRIPTION:
Stink Creek 87.0
END DESCRIPTION:
XS GIS Cut Line= 3
      1437704.98        6852338.      1438204.71      6852403.49
      1439341.48      6851707.33
#Sta/Elev= 30
    4496 2130.01  4576.7 2128.13  4717.9 2121.53  4758.2 2120.39  4769.4 2120.89
  4809.3 2118.93  4819.6 2117.88  4859.1 2115.13  4899.4 2109.94  4916.9 2109.24
    4922 2109.95    4948 2105.61  4949.9 2105.24  4954.7 2101.85  4955.2 2101.35
  4965.3 2101.85    4970 2105.99  4980.1 2107.91  5003.6 2108.53  5012.1  2104.1
  5024.9  2102.6  5034.4 2106.39  5055.7 2109.06    5077 2110.28  5240.2 2114.25
  5477.4 2116.82  5877.8 2117.65  6257.9  2120.6  6313.7 2121.45    6333 2123.03
#Mann= 8 ,-1 , 0
    4496     .07       0  4809.3     .16       0  4819.6     .07       0
    4948     .16       0  4954.7     .07       0  4965.3     .16       0
  5240.2     .07       0  6257.9    .035       0
Bank Sta=4954.7,4965.3
XS Rating Curve= 0 ,0
Exp/Cntr=0.3,0.1