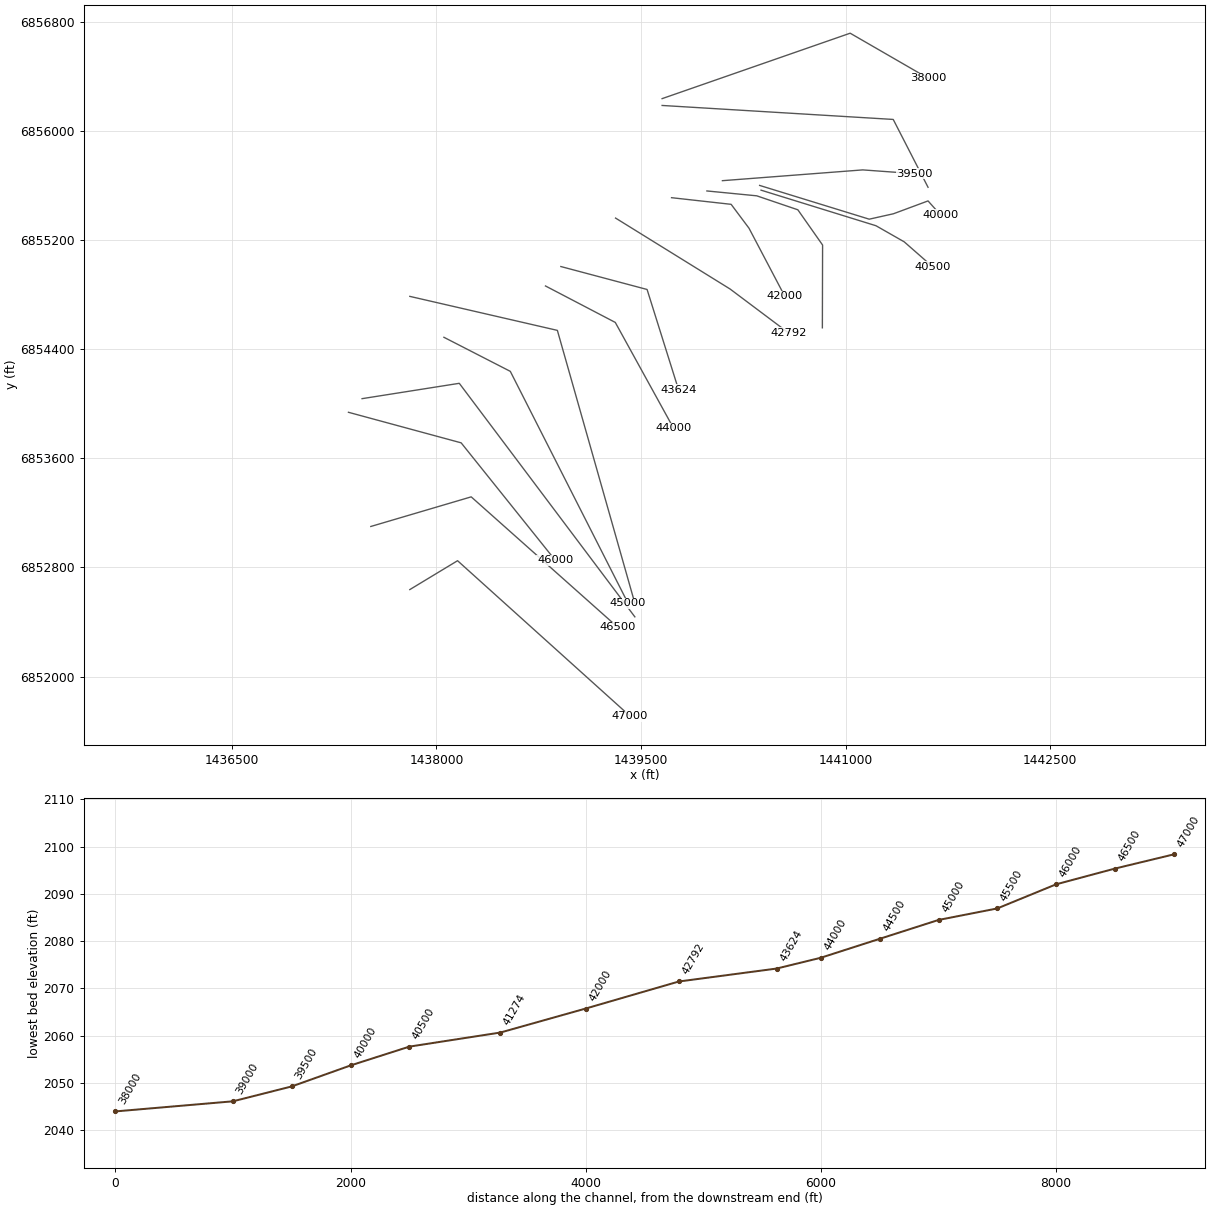
HEC-RAS study Stink Creek.prj: Stink Creek Base Level Engineering

--- Stink Creek.g01 (geometry) --- (continued)

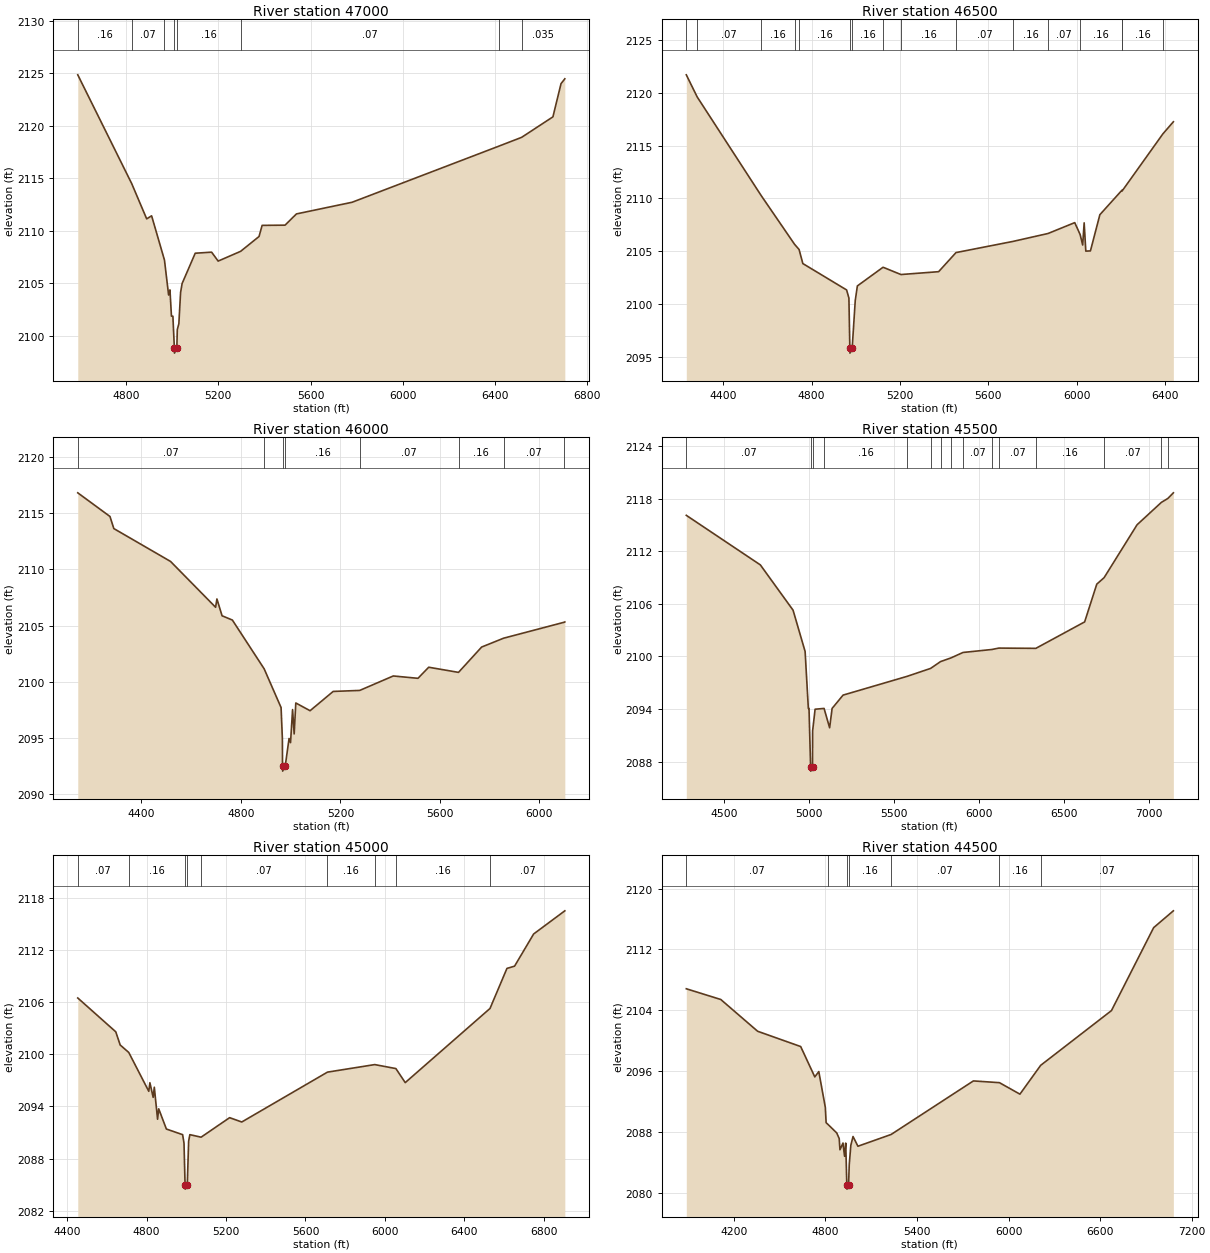
Type RM Length L Ch R = 1 ,47000   ,500,500,500
BEGIN DESCRIPTION:
Stink Creek 86.0
END DESCRIPTION:
XS GIS Cut Line= 3
      1437804.96      6852637.98      1438155.04      6852849.66
      1439420.07      6851709.97
#Sta/Elev= 30
  4590.9 2124.83  4824.9 2114.47  4889.7 2111.12  4911.1 2111.41  4966.8  2107.2
  4984.8 2103.87  4990.6 2104.36  4997.1 2101.86  5003.3 2101.86  5009.7 2098.84
  5010.2 2098.34  5020.4 2098.84  5022.5 2100.58  5029.2 2101.14  5036.7 2104.11
  5043.4 2104.97  5100.2 2107.85  5171.2 2107.95  5199.6  2107.1  5297.1 2108.03
  5376.8 2109.44  5390.3  2110.5  5489.6 2110.52    5539 2111.59  5780.4  2112.7
  6417.8 2118.05  6515.5 2118.88  6651.1 2120.83  6686.2 2123.99  6702.7 2124.45
#Mann= 8 ,-1 , 0
  4590.9     .16       0  4824.9     .07       0  4966.8     .16       0
  5009.7     .07       0  5020.4     .16       0  5297.1     .07       0
  6417.8     .16       0  6515.5    .035       0
Bank Sta=5009.7,5020.4
XS Rating Curve= 0 ,0
Exp/Cntr=0.3,0.1

Type RM Length L Ch R = 1 ,46500   ,500,500,500
BEGIN DESCRIPTION:
Stink Creek 85.0
END DESCRIPTION:
XS GIS Cut Line= 3
      1437518.92       6853100.7      1438255.05       6853317.9
      1439329.06      6852362.14
#Sta/Elev= 30
  4232.5 2121.72  4281.9 2119.62    4571 2110.29  4722.5 2105.66  4743.2 2105.16
  4760.1 2103.83  4958.2 2101.33  4968.7 2100.56  4972.9 2095.84  4973.4 2095.34
  4983.6 2095.84  4997.4 2100.32    5007 2101.71  5123.3 2103.48  5204.3 2102.79
  5374.9 2103.06  5453.5 2104.87  5711.8 2105.93  5870.3 2106.68  5991.2 2107.71
  6015.6 2106.58  6027.1 2105.59  6033.8 2107.69  6041.3 2105.01  6062.2 2105.03
  6104.9 2108.46  6204.8 2110.78    6206 2110.72  6390.5 2116.13  6437.7 2117.27
#Mann= 16 ,-1 , 0
  4232.5     .16       0  4281.9     .07       0    4571     .16       0
  4722.5     .07       0  4743.2     .16       0  4972.9     .07       0
  4983.6     .16       0  5123.3     .07       0  5204.3     .16       0
  5453.5     .07       0  5711.8     .16       0  5870.3     .07       0
  6015.6     .16       0  6204.8     .07       0    6206     .16       0
  6390.5     .07       0
Bank Sta=4972.9,4983.6
XS Rating Curve= 0 ,0
Exp/Cntr=0.3,0.1

Type RM Length L Ch R = 1 ,46000   ,500,500,500
BEGIN DESCRIPTION:
Stink Creek 84.0
END DESCRIPTION:
XS GIS Cut Line= 3
      1437355.01        6853938.      1438181.38      6853713.98
      1438870.67       6852853.9
#Sta/Elev= 30
  4143.8 2116.84  4273.3 2114.73  4288.8 2113.65  4516.8 2110.72    4698 2106.63
  4703.3 2107.37    4724 2105.87  4765.4 2105.49  4893.2 2101.14  4961.3 2097.68
  4966.5 2094.91  4967.1 2092.51  4967.6 2092.01  4978.3 2092.51  4993.4 2094.92
  4999.3 2094.55  5007.5  2097.5  5013.9 2095.33  5020.5 2098.09  5077.9  2097.4
  5170.8 2099.12  5277.5 2099.21  5412.4  2100.5  5511.7 2100.29  5554.9 2101.28
  5674.7 2100.82  5767.7 2103.08  5856.1 2103.87  6100.8  2105.3  6102.2 2105.32
#Mann= 8 ,-1 , 0
  4143.8     .07       0  4893.2     .16       0  4967.1     .07       0
  4978.3     .16       0  5277.5     .07       0  5674.7     .16       0
  5856.1     .07       0  6100.8     .16       0
Bank Sta=4967.1,4978.3
XS Rating Curve= 0 ,0
Exp/Cntr=0.3,0.1

Type RM Length L Ch R = 1 ,45500   ,500,500,500
BEGIN DESCRIPTION:
Stink Creek 83.0
END DESCRIPTION:
XS GIS Cut Line= 3
      1437454.96      6854037.99      1438167.63       6854150.5
      1439454.98      6852438.02
#Sta/Elev= 30
  4278.5 2116.12  4713.9 2110.46  4906.2 2105.29  4977.1 2100.57  4996.1 2094.07
    5000 2094.07  5009.4 2087.41  5009.9 2086.91  5020.6 2087.41  5021.2  2091.5
  5035.8 2093.98  5088.6 2094.07  5121.2 2091.86  5135.8 2094.07  5200.3 2095.59
  5577.9 2097.74    5715 2098.64  5773.6 2099.42    5835 2099.84  5905.6 2100.46
  6075.1  2100.8  6116.1 2100.96  6333.9 2100.93  6620.7 2103.95    6692 2108.26
  6735.1    2109  6928.9 2115.04  7071.9  2117.6  7110.2 2118.05  7142.4 2118.69
#Mann= 15 ,-1 , 0
  4278.5     .07       0  5009.4     .07       0  5020.6     .07       0
  5088.6     .16       0  5577.9     .07       0    5715     .16       0
  5773.6     .07       0    5835     .16       0  5905.6     .07       0
  6075.1     .16       0  6116.1     .07       0  6333.9     .16       0
  6735.1     .07       0  7071.9     .16       0  7110.2     .07       0
Bank Sta=5009.4,5020.6
XS Rating Curve= 0 ,0
Exp/Cntr=0.3,0.1

Type RM Length L Ch R = 1 ,45000   ,500,500,500
BEGIN DESCRIPTION:
Stink Creek 82.0
END DESCRIPTION:
XS GIS Cut Line= 3
      1438054.97      6854488.02      1438541.81      6854238.18
      1439405.02      6852537.96
#Sta/Elev= 30
  4452.8 2106.51  4644.3 2102.61  4666.5 2101.09  4709.7 2100.23  4810.6 2095.75
  4816.2 2096.74  4832.7 2095.05  4838.4 2096.22  4854.9 2092.53  4860.6 2093.73
  4899.3  2091.4  4981.1 2090.75  4988.1 2089.76  4993.4 2084.97  4993.9 2084.47
  5004.6 2084.97  5011.4    2090  5017.6 2090.75  5074.2 2090.46  5217.9 2092.71
  5279.1 2092.21  5710.8 2097.96  5949.2 2098.83  6055.7 2098.37  6102.7 2096.75
  6529.8  2105.3  6615.2 2109.92  6653.6 2110.18  6749.7 2113.89  6906.8 2116.56
#Mann= 9 ,-1 , 0
  4452.8     .07       0  4709.7     .16       0  4993.4     .07       0
  5004.6     .16       0  5074.2     .07       0  5710.8     .16       0
  5949.2     .07       0  6055.7     .16       0  6529.8     .07       0
Bank Sta=4993.4,5004.6
XS Rating Curve= 0 ,0
Exp/Cntr=0.3,0.1

Type RM Length L Ch R = 1 ,44500   ,500,500,500
BEGIN DESCRIPTION:
Stink Creek 81.0
END DESCRIPTION:
XS GIS Cut Line= 3
      1437804.96      6854788.01      1438886.91      6854538.69
      1439455.01      6852537.98
#Sta/Elev= 30
  3889.7 2106.83  4115.5 2105.42    4357 2101.24  4638.9 2099.23  4731.2 2095.24
  4757.5 2095.94  4800.3 2091.23  4805.4 2089.21  4816.2 2089.02  4874.9 2087.87
    4891 2087.14  4896.1 2085.66  4915.9 2086.54  4926.2  2084.8  4933.8 2086.53
  4941.1 2080.98  4941.6 2080.48  4952.3 2080.98    4957 2083.71  4967.3 2086.25
  4981.7  2087.4  5013.8 2086.12  5231.3 2087.67    5770 2094.71  5940.8 2094.48
  6074.8 2092.97  6210.7 2096.76  6674.4 2103.96  6950.7 2114.87  7079.8 2117.08
#Mann= 7 ,-1 , 0
  3889.7     .07       0  4816.2     .16       0  4941.1     .07       0
  4952.3     .16       0  5231.3     .07       0  5940.8     .16       0
  6210.7     .07       0
Bank Sta=4941.1,4952.3
XS Rating Curve= 0 ,0
Exp/Cntr=0.3,0.1

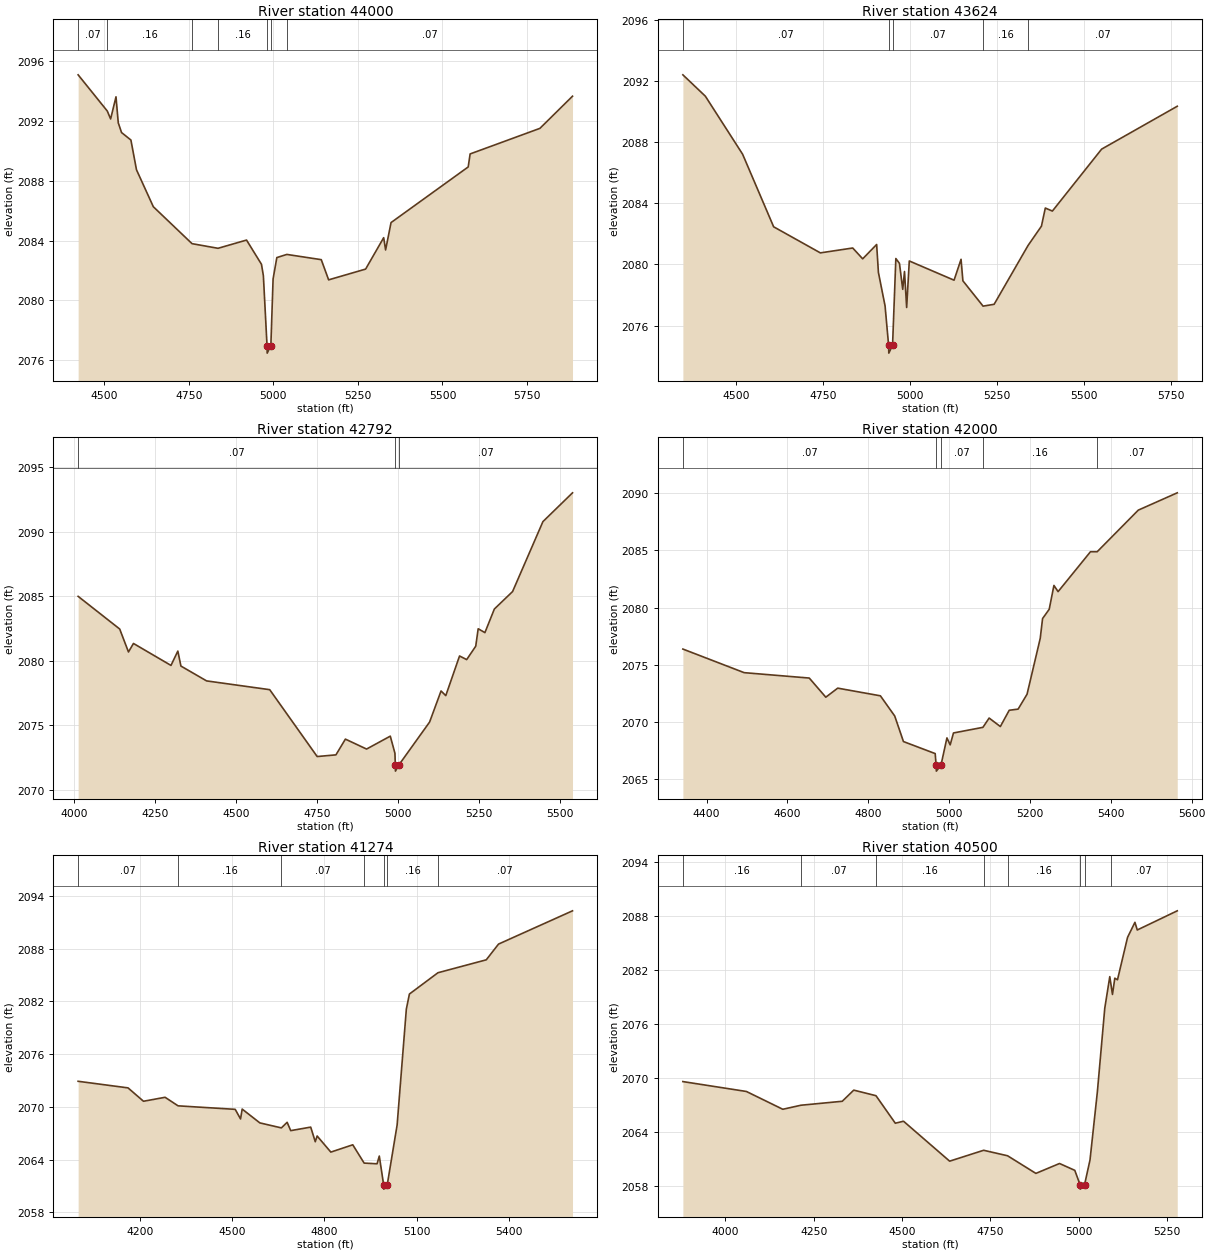
Type RM Length L Ch R = 1 ,44000   ,376,376,376
BEGIN DESCRIPTION:
Stink Creek 80.0
END DESCRIPTION:
XS GIS Cut Line= 3
       1438799.8      6854864.35      1439311.66      6854596.95
      1439738.44        6853822.
#Sta/Elev= 30
  4422.5 2095.09  4508.7 2092.67  4518.6 2092.14  4534.5 2093.62  4541.2 2091.88
  4550.9 2091.23  4578.6 2090.73  4595.1 2088.74  4644.9 2086.27  4759.4  2083.8
  4836.2 2083.49  4920.6 2084.04  4964.8 2082.42  4970.4 2081.65  4981.2 2076.98
  4981.7 2076.48  4992.5 2076.98  4999.1 2081.44  5010.2 2082.87  5039.8 2083.08
  5141.6 2082.73  5163.4 2081.38  5272.8  2082.1  5326.2  2084.2  5331.9 2083.38
    5348 2085.21  5576.2 2088.93  5581.9  2089.8  5788.3 2091.51  5884.7 2093.66
#Mann= 7 ,-1 , 0
  4422.5     .07       0  4508.7     .16       0  4759.4     .07       0
  4836.2     .16       0  4981.2     .07       0  4992.5     .16       0
  5039.8     .07       0
Bank Sta=4981.2,4992.5
XS Rating Curve= 0 ,0
Exp/Cntr=0.3,0.1

Type RM Length L Ch R = 1 ,43624   ,832,832,832
BEGIN DESCRIPTION:
Stink Creek 79.0
END DESCRIPTION:
XS GIS Cut Line= 3
      1438912.47      6855006.81      1439544.77      6854838.57
      1439775.15        6854105.
#Sta/Elev= 30
  4345.7 2092.43  4410.4 2091.03  4517.6 2087.23    4607 2082.47  4741.5 2080.76
  4834.7 2081.08  4863.3 2080.37  4903.5 2081.31  4908.6 2079.48  4927.8 2077.28
    4938 2074.69  4938.5 2074.19  4949.3 2074.69  4958.8 2080.39  4969.2 2080.07
  4978.6 2078.37  4983.7 2079.54  4989.9 2077.18  4997.5 2080.23  5126.4 2078.97
  5146.5 2080.34  5151.8 2078.93  5209.9 2077.27  5241.7 2077.39  5339.5 2081.25
  5377.9 2082.51  5389.1  2083.7  5409.4  2083.5  5551.2 2087.56  5768.9 2090.37
#Mann= 5 ,-1 , 0
  4345.7     .07       0    4938     .07       0  4949.3     .07       0
  5209.9     .16       0  5339.5     .07       0
Bank Sta=4938,4949.3
XS Rating Curve= 0 ,0
Exp/Cntr=0.3,0.1

Type RM Length L Ch R = 1 ,42792   ,792,792,792
BEGIN DESCRIPTION:
Stink Creek 78.0
END DESCRIPTION:
XS GIS Cut Line= 3
      1439313.64      6855362.21      1440153.61      6854841.84
      1440583.92      6854518.92
#Sta/Elev= 30
  4011.9 2084.99  4140.2 2082.46  4167.3 2080.68  4182.7 2081.34  4298.5 2079.64
  4319.7 2080.75  4329.2 2079.59  4408.4 2078.44  4603.3 2077.76  4749.8 2072.58
  4807.7 2072.71  4836.9 2073.93  4902.3 2073.16  4975.5 2074.16  4989.9 2072.83
  4990.9 2071.95  4991.4 2071.45  5002.6 2071.95  5096.8 2075.25  5132.2 2077.66
  5146.8  2077.3  5189.3 2080.37  5211.3 2080.09  5239.3 2081.13  5246.8 2082.48
  5267.6 2082.18  5296.8 2084.01    5353 2085.36  5446.7 2090.78    5538 2093.01
#Mann= 3 ,-1 , 0
  4011.9     .07       0  4990.9     .07       0  5002.6     .07       0
Bank Sta=4990.9,5002.6
XS Rating Curve= 0 ,0
Exp/Cntr=0.3,0.1

Type RM Length L Ch R = 1 ,42000   ,726,726,726
BEGIN DESCRIPTION:
Stink Creek 77.0
END DESCRIPTION:
XS GIS Cut Line= 4
      1439724.21      6855511.64      1440161.09        6855463.
      1440292.33      6855287.53      1440555.01      6854787.98
#Sta/Elev= 30
  4341.3 2076.38    4493 2074.32    4654 2073.85  4694.9 2072.18  4724.4 2072.97
    4830  2072.3  4865.4 2070.54    4887 2068.31  4965.5 2067.26  4967.9 2066.23
  4968.4 2065.73  4979.7 2066.23  4994.6 2068.63  5002.6 2068.02  5010.8 2069.06
  5083.6 2069.55    5099 2070.36  5126.7 2069.62  5148.7 2071.04  5170.7 2071.14
  5192.8 2072.44  5225.4 2077.31  5231.2 2079.04  5247.6 2079.85  5259.3 2081.93
  5269.6 2081.39  5349.7 2084.87  5366.3 2084.87    5468  2088.5  5564.4 2090.01
#Mann= 5 ,-1 , 0
  4341.3     .07       0  4967.9     .07       0  4979.7     .07       0
  5083.6     .16       0  5366.3     .07       0
Bank Sta=4967.9,4979.7
XS Rating Curve= 0 ,0
Exp/Cntr=0.3,0.1

Type RM Length L Ch R = 1 ,41274   ,774,774,774
BEGIN DESCRIPTION:
Stink Creek 76.0
END DESCRIPTION:
XS GIS Cut Line= 5
      1439983.41      6855561.08      1440348.94      6855525.34
      1440650.31      6855422.95      1440831.73      6855164.53
      1440830.14      6854557.43
#Sta/Elev= 30
  3998.7 2072.91  4161.1 2072.16  4211.3 2070.64  4281.6 2071.09  4323.8 2070.12
  4509.7 2069.72  4527.1 2068.63  4532.4 2069.75  4589.9 2068.18    4660 2067.61
  4678.7 2068.25  4690.3  2067.3  4755.4  2067.7  4770.2 2066.04  4776.3 2066.69
  4820.8 2064.86  4892.2 2065.69  4929.2 2063.61  4971.3 2063.53  4978.5 2064.41
  4992.6 2061.15  4993.1 2060.65  5004.4 2061.15  5036.5 2067.94  5066.5 2081.12
  5076.5 2082.83  5169.3 2085.25  5326.5 2086.72  5366.5 2088.51  5607.1 2092.29
#Mann= 7 ,-1 , 0
  3998.7     .07       0  4323.8     .16       0    4660     .07       0
  4929.2     .16       0  4992.6     .07       0  5004.4     .16       0
  5169.3     .07       0
Bank Sta=4992.6,5004.4
XS Rating Curve= 0 ,0
Exp/Cntr=0.3,0.1

Type RM Length L Ch R = 1 ,40500   ,500,500,500
BEGIN DESCRIPTION:
Stink Creek 74.0
END DESCRIPTION:
XS GIS Cut Line= 4
      1440380.47      6855566.85      1441223.25      6855306.01
      1441430.32      6855187.93       1441640.2       6855004.1
#Sta/Elev= 30
  3879.4 2069.63  4059.2 2068.53  4162.3 2066.55  4213.6    2067  4330.6 2067.44
  4363.2 2068.68  4426.1 2068.06  4480.8    2065  4504.1 2065.22  4634.6 2060.78
  4730.9 2061.99  4798.6 2061.38  4878.8 2059.42  4945.7 2060.52  4988.9 2059.76
  5003.8 2058.17  5004.3 2057.67  5016.6 2058.17    5032 2060.91  5052.9 2068.51
  5073.8 2077.79    5088  2081.3  5091.5 2080.39  5095.6 2079.32  5102.2 2081.13
  5109.8 2080.95  5138.3 2085.67  5159.2 2087.34  5165.8 2086.49    5279 2088.62
#Mann= 8 ,-1 , 0
  3879.4     .16       0  4213.6     .07       0  4426.1     .16       0
  4730.9     .07       0  4798.6     .16       0  5003.8     .07       0
  5016.6     .16       0  5091.5     .07       0
Bank Sta=5003.8,5016.6
XS Rating Curve= 0 ,0
Exp/Cntr=0.3,0.1

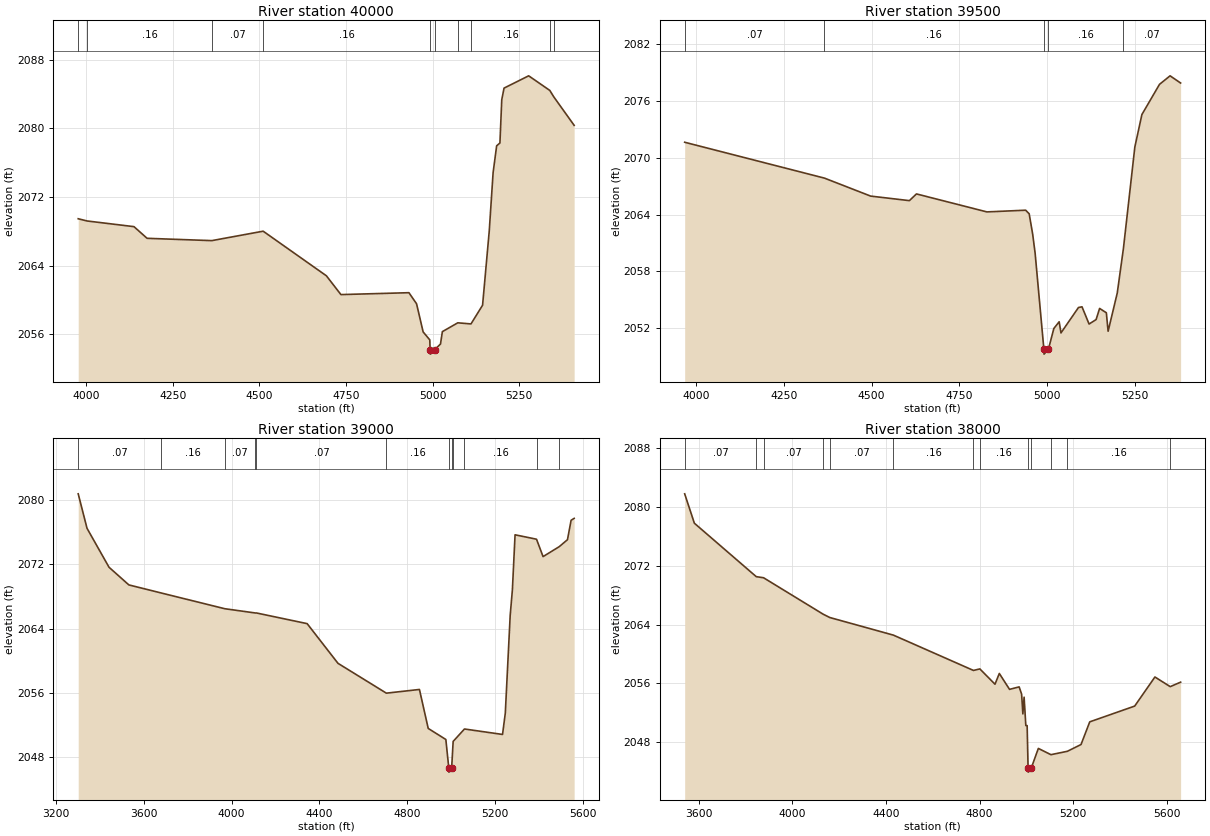
Type RM Length L Ch R = 1 ,40000   ,500,500,500
BEGIN DESCRIPTION:
Stink Creek 73.0
END DESCRIPTION:
XS GIS Cut Line= 5
       1440370.1      6855601.62      1441173.76      6855354.09
      1441351.73      6855393.96        1441605.        6855488.
      1441697.26      6855384.79
#Sta/Elev= 30
  3976.7 2069.47  4002.5 2069.21  4137.7 2068.55  4175.6 2067.19  4362.4 2066.92
  4510.7 2068.02  4693.3 2062.82  4735.2 2060.63  4931.6 2060.85  4953.6 2059.56
  4972.6 2056.28  4991.8 2055.35  4992.7 2054.19  4993.2 2053.69  5005.5 2054.19
  5022.7 2054.87  5028.1 2056.31  5072.6 2057.34  5110.7 2057.21  5144.2 2059.39
  5163.5 2068.06  5174.6 2074.84  5184.8 2077.97  5194.3  2078.3  5199.6 2083.35
  5206.2  2084.7  5277.3 2086.13  5338.3 2084.43  5349.6 2083.69  5408.6 2080.36
#Mann= 10 ,-1 , 0
  3976.7     .07       0  4002.5     .16       0  4362.4     .07       0
  4510.7     .16       0  4992.7     .07       0  5005.5     .16       0
  5072.6     .07       0  5110.7     .16       0  5338.3     .07       0
  5349.6     .16       0
Bank Sta=4992.7,5005.5
XS Rating Curve= 0 ,0
Exp/Cntr=0.3,0.1

Type RM Length L Ch R = 1 ,39500   ,500,500,500
BEGIN DESCRIPTION:
Stink Creek 72.0
END DESCRIPTION:
XS GIS Cut Line= 3
      1440097.18      6855636.39      1441126.25      6855715.48
      1441504.95        6855688.
#Sta/Elev= 30
  3967.9 2071.64  4365.8 2067.85  4497.3 2065.95  4607.6 2065.47  4627.7 2066.18
  4828.2 2064.28  4938.6 2064.46  4948.6 2064.08  4958.6 2061.92  4965.6 2059.89
  4990.5 2049.75    4991 2049.25  5003.3 2049.75  5018.8 2051.96    5034 2052.67
  5039.1 2051.49    5089 2054.18    5099 2054.25  5119.1 2052.43  5139.1  2052.9
  5149.1 2054.08  5168.3 2053.62  5173.3 2051.67  5199.3  2055.7  5216.9 2060.42
  5249.4 2071.14  5269.5 2074.57  5319.6 2077.76  5349.7 2078.66  5379.7  2077.9
#Mann= 5 ,-1 , 0
  3967.9     .07       0  4365.8     .16       0  4990.5     .07       0
  5003.3     .16       0  5216.9     .07       0
Bank Sta=4990.5,5003.3
XS Rating Curve= 0 ,0
Exp/Cntr=0.3,0.1

Type RM Length L Ch R = 1 ,39000   ,1000,1000,1000
BEGIN DESCRIPTION:
Stink Creek 71.0
END DESCRIPTION:
XS GIS Cut Line= 3
      1439654.96        6856188.      1441349.77      6856085.48
      1441604.99      6855588.03
#Sta/Elev= 30
  3302.1 2080.81  3342.2 2076.51  3442.4 2071.65  3532.6 2069.45  3678.8 2068.45
  3969.2 2066.48  4107.9 2065.95  4113.3 2065.95    4344 2064.62  4484.3 2059.67
  4704.4 2055.95    4855 2056.41    4895 2051.55  4975.2 2050.17  4988.7  2046.6
  4989.2  2046.1  5001.6  2046.6  5008.4 2049.93    5060 2051.48  5233.2  2050.8
  5245.8 2053.46    5268 2065.64  5278.1 2068.86  5290.2  2075.7  5387.8 2075.15
  5417.7 2072.98  5491.2 2074.22  5528.7 2075.09  5545.2 2077.51  5559.1 2077.75
#Mann= 12 ,-1 , 0
  3302.1     .07       0  3678.8     .16       0  3969.2     .07       0
  4107.9     .16       0  4113.3     .07       0  4704.4     .16       0
  4988.7     .07       0  5001.6     .16       0  5008.4     .07       0
    5060     .16       0  5387.8     .07       0  5491.2     .16       0
Bank Sta=4988.7,5001.6
XS Rating Curve= 0 ,0
Exp/Cntr=0.3,0.1

Type RM Length L Ch R = 1 ,38000   ,722,722,722
BEGIN DESCRIPTION:
Stink Creek 70.0
END DESCRIPTION:
XS GIS Cut Line= 3
      1439654.97      6856237.99      1441033.97      6856717.84
      1441604.96      6856388.02
#Sta/Elev= 30
  3539.9 2081.76  3581.3 2077.77  3845.8 2070.51    3877 2070.36  4131.8 2065.41
  4160.1 2064.96  4431.8 2062.57  4774.2 2057.77  4801.4 2057.98  4866.1  2055.9
  4884.6 2057.36  4928.3  2055.2  4969.3 2055.54  4979.9 2054.55  4985.2 2051.87
  4990.5 2054.14  4997.9 2050.28  5003.5 2050.28  5007.6 2044.46  5008.1 2043.96
  5020.5 2044.46  5051.4 2047.18  5105.1 2046.33  5175.5 2046.79  5233.8 2047.71
  5271.1 2050.79  5463.1 2052.93  5549.6 2056.88  5615.1 2055.57  5659.4 2056.18
#Mann= 13 ,-1 , 0
  3539.9     .07       0  3845.8     .16       0    3877     .07       0
  4131.8     .16       0  4160.1     .07       0  4431.8     .16       0
  4774.2     .07       0  4801.4     .16       0  5007.6     .07       0
  5020.5     .16       0  5105.1     .07       0  5175.5     .16       0
  5615.1     .07       0
Bank Sta=5007.6,5020.5
XS Rating Curve= 0 ,0
Exp/Cntr=0.3,0.1