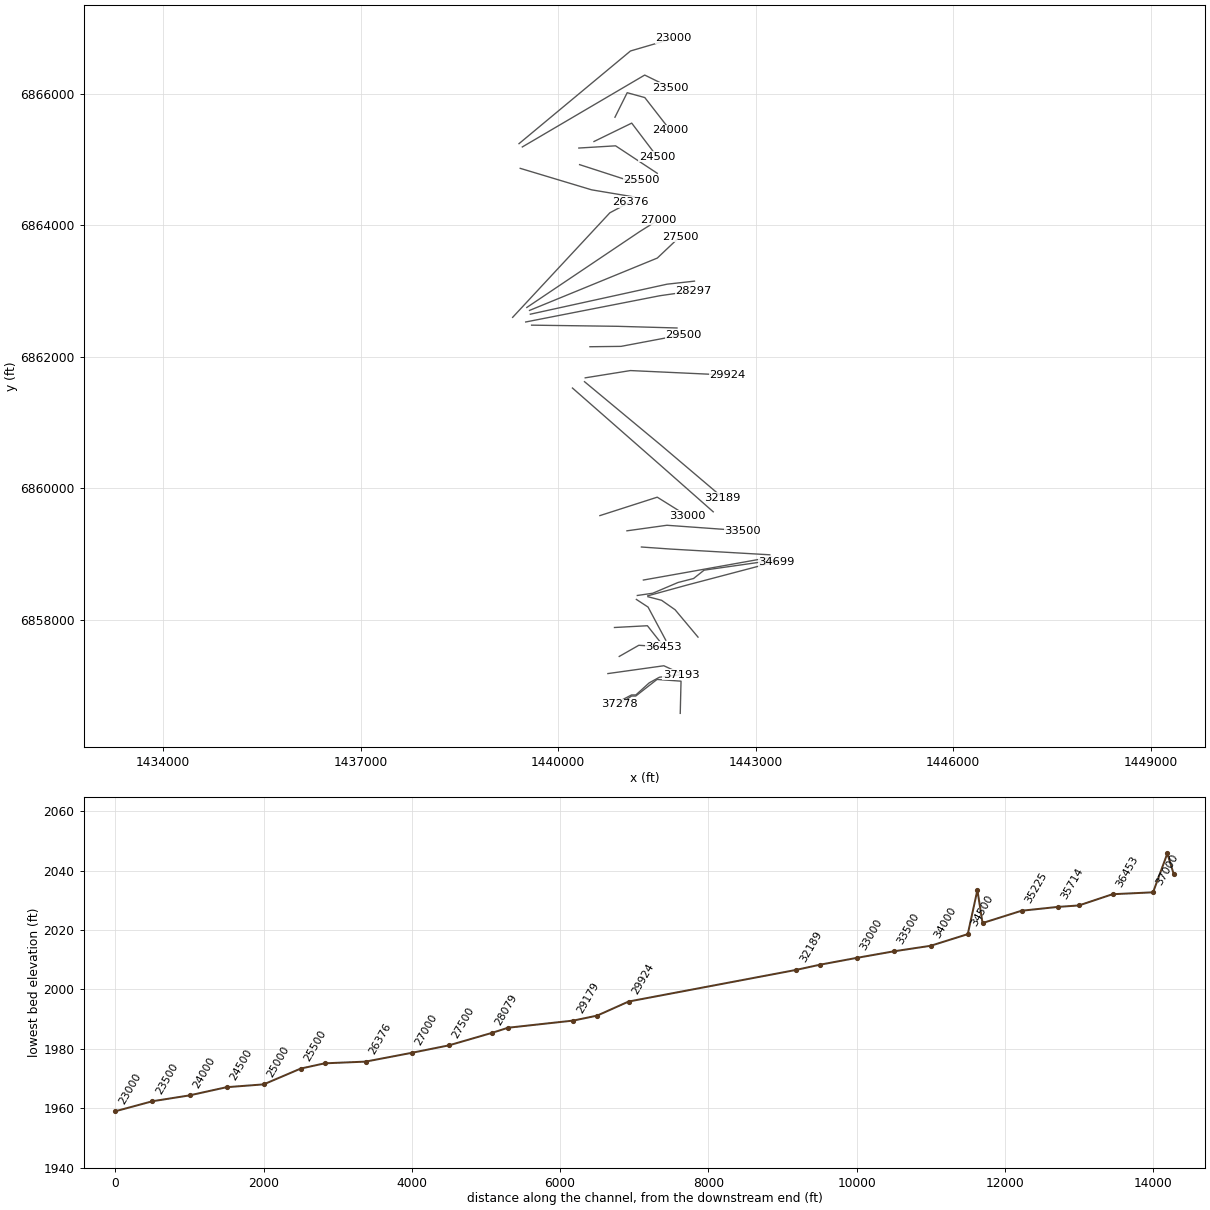
HEC-RAS study Stink Creek.prj: Stink Creek Base Level Engineering

--- Stink Creek.g01 (geometry) --- (continued)

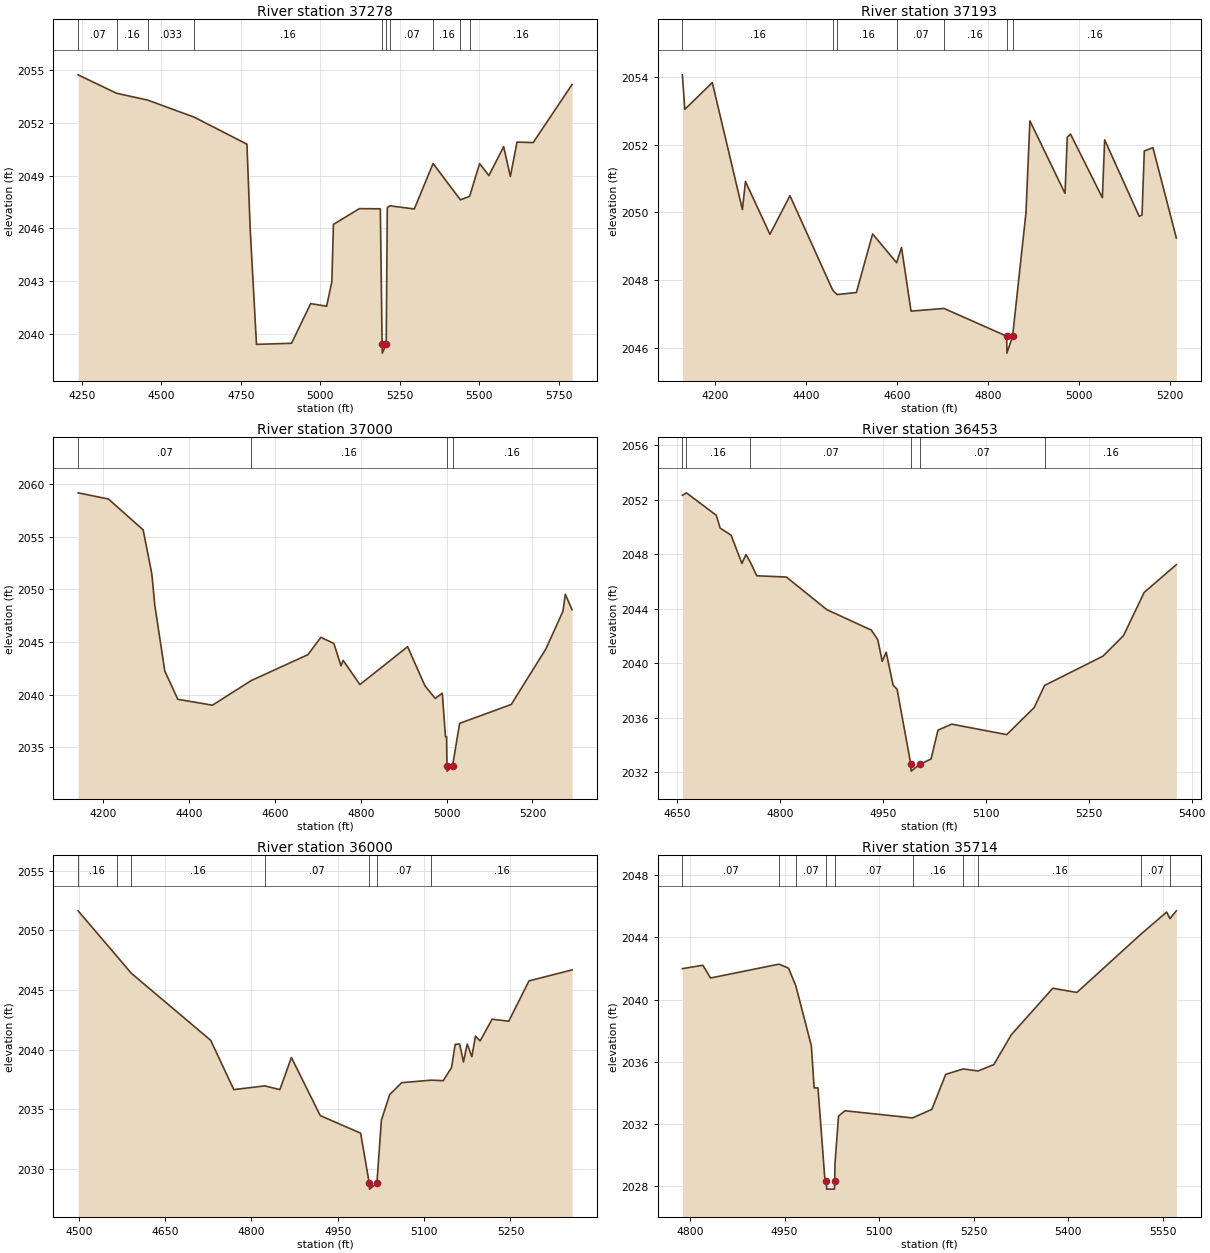
Type RM Length L Ch R = 1 ,37278   ,85,85,85
BEGIN DESCRIPTION:
Stink Creek 69.0
END DESCRIPTION:
XS GIS Cut Line= 6
      1441854.19      6856583.43      1441866.22      6857072.66
      1441501.32      6857098.87      1441178.76      6856846.86
      1441114.96      6856846.86      1440932.21      6856721.84
#Sta/Elev= 30
  4238.6 2054.75  4359.4  2053.7  4457.4 2053.31  4603.4 2052.34  4769.3  2050.8
  4779.3 2046.05  4799.3  2039.4  4909.5 2039.46  4969.6 2041.72  5019.8 2041.57
  5036.2 2042.97  5041.2 2046.23  5122.8 2047.13  5188.6 2047.12  5194.2  2039.4
  5194.7  2038.9  5207.1  2039.4  5210.5 2047.19    5219 2047.29  5295.4 2047.11
  5354.4  2049.7  5440.4 2047.63  5469.3 2047.83  5500.7  2049.7  5529.8 2049.01
  5576.3 2050.66  5597.3 2048.96  5618.3 2050.92    5669 2050.89  5791.3  2054.2
#Mann= 10 ,-1 , 0
  4238.6     .07       0  4359.4     .16       0  4457.4    .033       0
  4603.4     .16       0  5194.2     .07       0  5207.1     .16       0
    5219     .07       0  5354.4     .16       0  5440.4     .07       0
  5469.3     .16       0
Bank Sta=5194.2,5207.1
XS Rating Curve= 0 ,0
Exp/Cntr=0.3,0.1

Type RM Length L Ch R = 1 ,37193   ,193,193,193
BEGIN DESCRIPTION:
Stink Creek 4141
END DESCRIPTION:
XS GIS Cut Line= 6
      1440902.17      6856752.17      1441114.01       6856863.3
      1441179.98       6856863.3       1441383.1      6857047.33
      1441537.62      6857132.39      1441866.09      6857171.87
#Sta/Elev= 30
  4127.4 2054.06  4132.7 2053.04  4193.2 2053.83  4259.4 2050.08  4266.1 2050.91
  4319.9 2049.35    4364 2050.49    4458  2047.7  4467.7 2047.57  4510.1 2047.63
  4545.8 2049.36  4598.6 2048.51  4609.4 2048.96  4630.3 2047.08  4702.9 2047.16
  4840.7 2046.34  4841.2 2045.84  4853.7 2046.34  4883.1 2049.98  4891.8  2052.7
    4969 2050.56    4974 2052.22  4981.1 2052.31  5051.2 2050.43  5056.2 2052.14
  5132.2 2049.88  5138.4 2049.92  5143.4 2051.81  5162.4 2051.91  5213.9 2049.24
#Mann= 7 ,-1 , 0
  4127.4     .16       0    4458     .07       0  4467.7     .16       0
  4598.6     .07       0  4702.9     .16       0  4840.7     .07       0
  4853.7     .16       0
Bank Sta=4840.7,4853.7
XS Rating Curve= 0 ,0
Exp/Cntr=0.3,0.1

Type RM Length L Ch R = 1 ,37000   ,547,547,547
BEGIN DESCRIPTION:
Stink Creek 68.0
END DESCRIPTION:
XS GIS Cut Line= 3
        1440755.        6857188.      1441604.93      6857306.85
      1441870.48      6857184.69
#Sta/Elev= 30
  4141.8 2059.19  4212.5  2058.6  4293.3 2055.67  4313.5 2051.48  4320.4 2048.51
  4343.7 2042.24    4374 2039.56  4454.8    2039    4545 2041.34    4677  2043.8
  4707.2 2045.45  4737.5 2044.87  4754.1 2042.74  4759.2 2043.26  4798.1 2040.96
  4909.2 2044.56  4949.6 2040.85  4973.5 2039.64    4990 2040.14  4997.5    2036
    5000    2036  5000.9 2033.23  5001.4 2032.73  5013.9 2033.23  5030.4 2037.27
  5150.7 2039.07  5231.2 2044.34  5271.1 2047.93  5276.6 2049.55  5292.3 2048.07
#Mann= 4 ,-1 , 0
  4141.8     .07       0    4545     .16       0  5000.9     .07       0
  5013.9     .16       0
Bank Sta=5000.9,5013.9
XS Rating Curve= 0 ,0
Exp/Cntr=0.3,0.1

Type RM Length L Ch R = 1 ,36453   ,453,453,453
BEGIN DESCRIPTION:
Stink Creek 67.1
END DESCRIPTION:
XS GIS Cut Line= 3
      1440927.48      6857448.35      1441224.91      6857617.97
       1441601.8      6857593.31
#Sta/Elev= 30
  4657.6 2052.34  4663.5 2052.52    4707 2050.87  4712.7 2049.93  4728.6 2049.41
  4744.4 2047.33  4750.2 2047.99  4756.3 2047.46    4766 2046.43  4809.2 2046.34
  4868.3 2043.94  4933.1 2042.44  4942.5 2041.73  4948.9 2040.15  4954.7 2040.82
  4964.8  2038.4  4970.6  2038.1  4990.6 2032.59  4991.1 2032.09  5003.7 2032.59
  5020.1 2032.98  5030.2  2035.1  5050.2 2035.54  5130.4 2034.77  5170.5 2036.76
  5185.6 2038.38  5270.7 2040.53  5300.7 2042.04  5330.8 2045.21  5377.7 2047.25
#Mann= 6 ,-1 , 0
  4657.6     .07       0  4663.5     .16       0  4756.3     .07       0
  4990.6     .07       0  5003.7     .07       0  5185.6     .16       0
Bank Sta=4990.6,5003.7
XS Rating Curve= 0 ,0
Exp/Cntr=0.3,0.1

Type RM Length L Ch R = 1 ,36000   ,286,286,286
BEGIN DESCRIPTION:
Stink Creek 67.0
END DESCRIPTION:
XS GIS Cut Line= 3
        1440855.        6857888.      1441355.28      6857914.79
      1441576.74      6857634.78
#Sta/Elev= 30
    4499 2051.63  4565.7 2047.86  4591.6 2046.39  4729.3 2040.78  4769.4 2036.65
  4823.3 2036.96  4849.5 2036.65  4869.5 2039.34  4919.6 2034.47  4989.7    2033
  5004.7 2028.81  5005.2 2028.31    5018 2028.81  5025.8 2034.09  5040.2 2036.23
    5061 2037.23  5112.2 2037.44  5133.2  2037.4  5147.6 2038.49    5154 2040.44
  5161.7 2040.47  5168.4 2038.96  5174.8 2040.47  5182.9 2039.41  5189.2 2041.13
  5197.3 2040.73  5218.1 2042.55    5247 2042.38  5282.2 2045.76    5357 2046.68
#Mann= 7 ,-1 , 0
    4499     .16       0  4565.7     .07       0  4591.6     .16       0
  4823.3     .07       0  5004.7     .07       0    5018     .07       0
  5112.2     .16       0
Bank Sta=5004.7,5018
XS Rating Curve= 0 ,0
Exp/Cntr=0.3,0.1

Type RM Length L Ch R = 1 ,35714   ,489,489,489
BEGIN DESCRIPTION:
Stink Creek 66.2
END DESCRIPTION:
XS GIS Cut Line= 3
      1441187.79      6858314.24      1441365.32      6858198.18
       1441634.6      6857694.44
#Sta/Elev= 30
  4787.9 2041.99  4820.4 2042.21  4832.5 2041.39  4941.2 2042.28  4956.2 2042.02
  4967.6 2040.91  4992.4 2037.03  4996.8 2034.32  5002.9 2034.32  5013.6 2028.57
  5016.2 2028.31  5016.7 2027.81    5029 2027.81  5029.5 2028.31  5029.8 2029.42
  5035.5 2032.51  5045.6 2032.85  5152.8 2032.39  5183.5 2032.94  5205.4 2035.19
  5233.1 2035.54  5256.9 2035.41  5281.8 2035.82  5309.5 2037.74  5375.3 2040.73
  5413.5 2040.46  5515.3 2044.22  5555.8 2045.63  5561.1 2045.21  5571.2 2045.71
#Mann= 10 ,-1 , 0
  4787.9     .07       0  4941.2     .16       0  4967.6     .07       0
  5016.2     .07       0  5029.5     .07       0  5152.8     .16       0
  5233.1     .07       0  5256.9     .16       0  5515.3     .07       0
  5561.1     .16       0
Bank Sta=5016.2,5029.5
XS Rating Curve= 0 ,0
Exp/Cntr=0.3,0.1

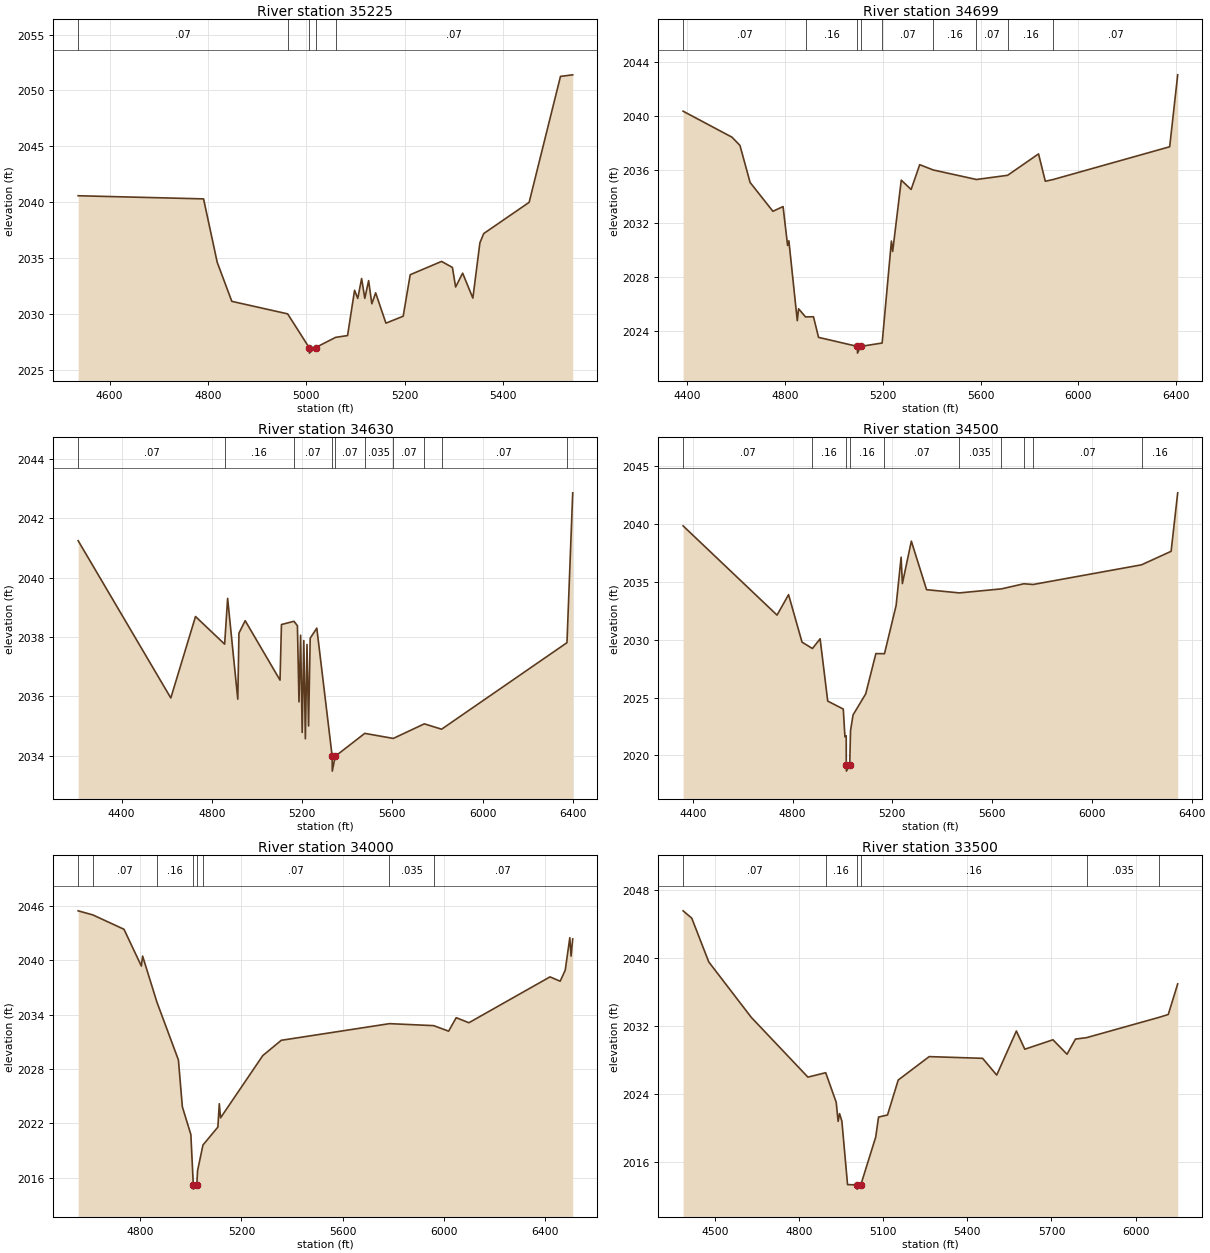
Type RM Length L Ch R = 1 ,35225   ,526,526,526
BEGIN DESCRIPTION:
Stink Creek 66.1
END DESCRIPTION:
XS GIS Cut Line= 4
      1441364.21      6858355.19      1441570.99      6858301.19
       1441776.1      6858157.58      1442124.24      6857741.78
#Sta/Elev= 30
  4535.9 2040.59  4791.1 2040.31  4818.9 2034.64  4848.6 2031.15  4962.2 2030.03
  5005.9 2027.02  5006.4 2026.52  5019.2 2027.02  5059.9 2027.93  5084.1 2028.09
  5098.4 2032.14  5104.9 2031.41  5112.7 2033.19  5119.2 2031.42    5127    2033
  5133.5 2030.93  5141.3 2031.91  5162.2  2029.2  5197.3 2029.82  5211.6 2033.53
  5275.4 2034.72  5297.5 2034.18    5304 2032.43  5318.3 2033.67  5339.1 2031.44
  5353.4 2036.38  5361.2 2037.21  5453.6    2040  5517.4 2051.26  5542.3  2051.4
#Mann= 5 ,-1 , 0
  4535.9     .07       0  4962.2    .033       0  5005.9    .033       0
  5019.2    .033       0  5059.9     .07       0
Bank Sta=5005.9,5019.2
XS Rating Curve= 0 ,0
Exp/Cntr=0.3,0.1

Type RM Length L Ch R = 1 ,34699   ,69,69,69
BEGIN DESCRIPTION:
Stink Creek 66.0
END DESCRIPTION:
XS GIS Cut Line= 3
      1441360.77      6858369.09      1441955.68      6858532.34
      1443315.42       6858890.4
#Sta/Elev= 30
  4383.1 2040.33  4583.1  2038.4  4615.6 2037.79  4657.1 2035.04  4750.4  2032.9
  4791.9 2033.25  4810.5 2030.36  4815.7 2030.71  4850.1 2024.78  4855.3 2025.66
  4883.8 2025.06  4916.3 2025.07  4937.1 2023.54  5095.9 2022.87  5096.4 2022.37
  5109.6 2022.87  5197.2 2023.12  5235.1 2030.69  5240.3 2029.92  5275.4 2035.21
  5315.7 2034.52  5350.9 2036.36  5405.6 2035.97  5582.8 2035.26  5710.4 2035.57
  5836.9 2037.16  5864.6 2035.13    5897 2035.26  6373.3 2037.69  6406.1 2043.03
#Mann= 9 ,-1 , 0
  4383.1     .07       0  4883.8     .16       0  5095.9     .07       0
  5109.6     .16       0  5197.2     .07       0  5405.6     .16       0
  5582.8     .07       0  5710.4     .16       0    5897     .07       0
Bank Sta=5095.9,5109.6
XS Rating Curve= 0 ,0
Exp/Cntr=0.3,0.1

Type RM Length L Ch R = 1 ,34630   ,130,130,130
BEGIN DESCRIPTION:
Stink Creek 65.1
END DESCRIPTION:
XS GIS Cut Line= 6
       1441202.3      6858374.38      1441436.85      6858408.61
      1441819.39      6858571.34      1442056.81      6858632.28
      1442216.72      6858759.13      1443290.75      6858911.98
#Sta/Elev= 30
  4207.8 2041.24  4618.5 2035.95    4728 2038.69  4857.1 2037.76  4870.3  2039.3
  4915.4 2035.91  4920.5 2038.13  4948.2 2038.55  5102.6 2036.55  5108.9 2038.42
  5164.2 2038.53  5179.7 2038.38  5186.6 2035.82  5193.8 2038.06  5200.8 2034.79
    5208 2037.88  5214.9 2034.58  5222.1 2037.75  5229.1 2035.01  5236.3 2037.96
  5265.6  2038.3  5333.7 2033.99  5334.2 2033.49  5347.4 2033.99  5478.2 2034.76
  5604.6 2034.59  5742.2 2035.08  5818.7  2034.9  6374.4 2037.81  6399.9 2042.85
#Mann= 10 ,-1 , 0
  4207.8     .07       0  4857.1     .16       0  5164.2     .07       0
  5333.7     .07       0  5347.4     .07       0  5478.2    .035       0
  5604.6     .07       0  5742.2     .16       0  5818.7     .07       0
  6374.4     .16       0
Bank Sta=5333.7,5347.4
XS Rating Curve= 0 ,0
Exp/Cntr=0.3,0.1

Type RM Length L Ch R = 1 ,34500   ,500,500,500
BEGIN DESCRIPTION:
Stink Creek 65.0
END DESCRIPTION:
XS GIS Cut Line= 3
      1441294.27      6858609.01      1441922.93      6858720.65
      1443245.97      6858957.67
#Sta/Elev= 30
  4361.5 2039.86    4738 2032.14  4784.2 2033.91  4838.2  2029.8  4879.9 2029.25
  4910.7 2030.09  4941.2  2024.7  5003.6 2024.01  5010.2 2021.62  5015.3  2021.7
  5015.6 2019.14  5016.1 2018.64  5029.3 2019.14  5032.6 2022.14  5042.7  2023.5
  5093.5 2025.33  5134.2 2028.81  5168.7  2028.8  5215.4 2032.98  5235.4 2037.15
  5240.5 2034.87  5276.4 2038.54  5337.4 2034.34  5468.9 2034.06  5637.7 2034.41
  5727.3 2034.85  5764.8 2034.79  6199.1 2036.49  6317.7 2037.66  6344.1 2042.72
#Mann= 10 ,-1 , 0
  4361.5     .07       0  4879.9     .16       0  5015.6     .07       0
  5029.3     .16       0  5168.7     .07       0  5468.9    .035       0
  5637.7     .07       0  5727.3     .16       0  5764.8     .07       0
  6199.1     .16       0
Bank Sta=5015.6,5029.3
XS Rating Curve= 0 ,0
Exp/Cntr=0.3,0.1

Type RM Length L Ch R = 1 ,34000   ,500,500,500
BEGIN DESCRIPTION:
Stink Creek 64.0
END DESCRIPTION:
XS GIS Cut Line= 3
      1441264.33      6859110.77      1441708.53      6859079.51
      1443214.52      6858992.51
#Sta/Elev= 30
  4554.7 2045.48  4612.7 2045.03  4735.8 2043.44  4804.4 2039.38  4809.4 2040.48
  4865.9 2035.39  4950.8    2029  4966.4 2023.82    5000 2020.75  5009.6 2015.22
  5010.1 2014.72  5023.4 2015.22  5026.5 2016.76  5047.7 2019.59  5106.7 2021.58
  5112.3 2024.16  5117.3  2022.6  5284.1 2029.48  5357.1 2031.17  5784.6 2033.01
  5959.3 2032.79  6018.2 2032.18  6048.2 2033.67  6098.3 2033.11  6418.8 2038.18
  6458.9  2037.7  6478.9 2038.92    6497 2042.51    6502 2040.48  6508.5 2042.37
#Mann= 8 ,-1 , 0
  4554.7     .16       0  4612.7     .07       0  4865.9     .16       0
  5009.6     .07       0  5023.4     .16       0  5047.7     .07       0
  5784.6    .035       0  5959.3     .07       0
Bank Sta=5009.6,5023.4
XS Rating Curve= 0 ,0
Exp/Cntr=0.3,0.1

Type RM Length L Ch R = 1 ,33500   ,500,500,500
BEGIN DESCRIPTION:
Stink Creek 63.0
END DESCRIPTION:
XS GIS Cut Line= 3
      1441044.47      6859356.77      1441651.55      6859441.06
      1442798.49      6859358.55
#Sta/Elev= 30
  4387.1 2045.54  4417.9 2044.68  4478.5 2039.54  4629.9 2033.03  4831.9    2026
  4895.3 2026.52  4932.8 2023.04  4939.6  2020.8  4944.7 2021.71    4953 2020.82
  4973.2 2013.37  5006.6 2013.34  5007.1 2012.84  5020.4 2013.34  5073.6 2018.96
  5083.7 2021.31  5115.6 2021.55  5153.8 2025.66  5264.1 2028.41  5454.6 2028.21
  5504.8 2026.24  5574.9 2031.42    5605 2029.28  5705.3 2030.39  5755.4 2028.69
  5785.5 2030.47  5825.3 2030.64  6084.1 2033.03  6116.3 2033.36  6149.9 2036.96
#Mann= 6 ,-1 , 0
  4387.1     .07       0  4895.3     .16       0  5006.6     .07       0
  5020.4     .16       0  5825.3    .035       0  6084.1     .07       0
Bank Sta=5006.6,5020.4
XS Rating Curve= 0 ,0
Exp/Cntr=0.3,0.1

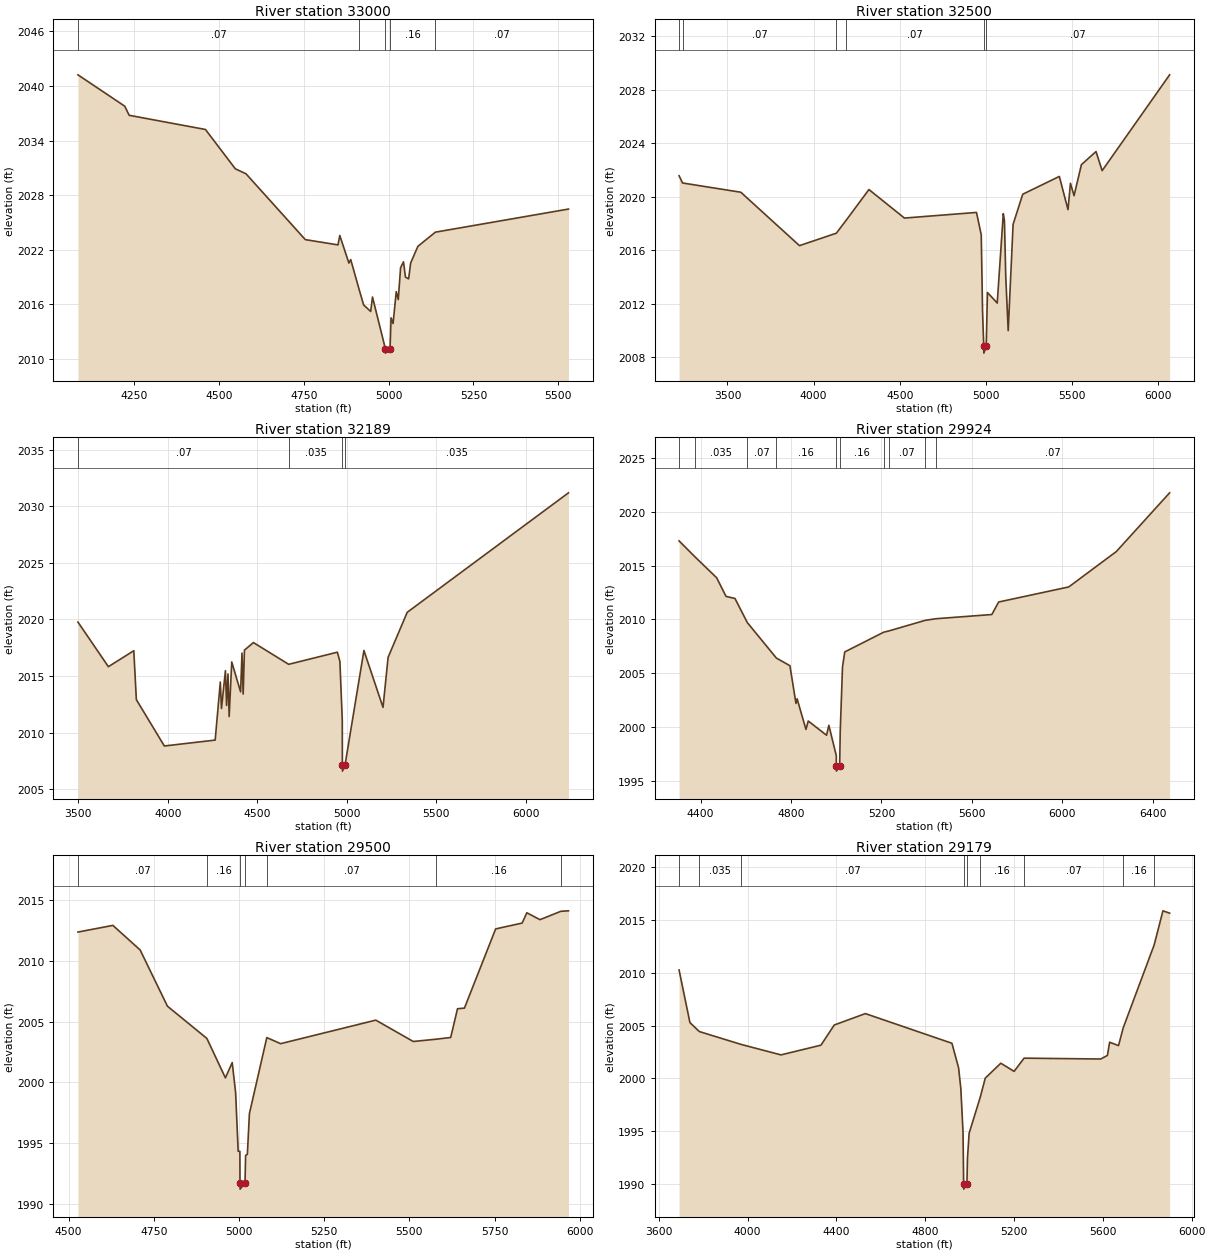
Type RM Length L Ch R = 1 ,33000   ,500,500,500
BEGIN DESCRIPTION:
Stink Creek 62.0
END DESCRIPTION:
XS GIS Cut Line= 3
      1440633.59      6859587.71      1441504.95      6859867.58
      1441954.57      6859586.96
#Sta/Elev= 30
  4084.8 2041.23  4222.8 2037.78  4235.7 2036.78  4460.5 2035.22  4548.4  2030.9
  4579.9 2030.35  4754.7 2023.11    4851 2022.53  4856.2 2023.57  4883.1 2020.53
  4888.4 2020.92  4913.4 2017.61  4926.5 2015.93  4947.3 2015.21  4952.6  2016.8
  4990.4 2011.13  4990.9 2010.63  5004.3 2011.13  5007.3 2014.51  5013.2 2013.88
  5022.6 2017.39  5028.5 2016.52  5035.4 2020.02  5043.9 2020.67  5049.8 2018.98
    5059  2018.8  5065.1 2020.55  5086.3 2022.37  5137.8 2023.93    5530 2026.47
#Mann= 5 ,-1 , 0
  4084.8     .07       0  4913.4     .16       0  4990.4     .07       0
  5004.3     .16       0  5137.8     .07       0
Bank Sta=4990.4,5004.3
XS Rating Curve= 0 ,0
Exp/Cntr=0.3,0.1

Type RM Length L Ch R = 1 ,32500   ,311,311,311
BEGIN DESCRIPTION:
Stink Creek 61.0
END DESCRIPTION:
XS GIS Cut Line= 3
      1440216.61      6861525.83      1441555.29      6860351.44
      1442355.29      6859645.25
#Sta/Elev= 30
  3219.2 2021.56  3239.5 2021.02  3577.6 2020.33  3918.2 2016.34  4132.4 2017.27
  4190.1 2018.25  4321.5 2020.53  4527.5  2018.4  4945.9 2018.82  4973.5 2017.15
  4981.1 2011.46  4988.1 2008.81  4988.6 2008.31  5002.4 2008.81  5009.5 2012.84
  5066.3 2012.05  5101.5 2018.73  5108.2 2018.21  5115.8 2014.04    5130 2009.99
  5158.4 2017.93  5214.4 2020.18  5426.9 2021.51  5477.2 2019.03  5491.4    2021
  5512.3 2020.07    5555 2022.39  5639.9 2023.37  5675.4 2021.94  6067.1  2029.1
#Mann= 6 ,-1 , 0
  3219.2    .045       0  3239.5     .07       0  4132.4    .035       0
  4190.1     .07       0  4988.1     .07       0  5002.4     .07       0
Bank Sta=4988.1,5002.4
XS Rating Curve= 0 ,0
Exp/Cntr=0.3,0.1

Type RM Length L Ch R = 1 ,32189   ,2265,2265,2265
BEGIN DESCRIPTION:
Stink Creek 60.0
END DESCRIPTION:
XS GIS Cut Line= 3
      1440399.83      6861622.08        1441555.      6860662.56
      1442498.57      6859862.03
#Sta/Elev= 30
  3498.3 2019.77  3668.3 2015.83  3810.2 2017.24  3824.5 2012.92  3980.8 2008.83
  4264.6 2009.35  4293.3 2014.48  4299.8 2012.14  4321.9 2015.48  4328.4 2012.41
  4336.2 2015.19  4342.7 2011.43  4357.1 2016.25  4406.5 2013.61  4414.4 2017.03
  4420.9 2013.41    4428 2017.29  4478.2 2017.96  4675.1 2016.04  4946.9 2017.11
    4961  2016.3  4974.3 2011.12  4974.9 2007.11  4975.4 2006.61  4989.3 2007.11
  5095.2 2017.26  5201.8 2012.24  5230.3 2016.66  5336.9 2020.63  6237.4 2031.18
#Mann= 4 ,-1 , 0
  3498.3     .07       0  4675.1    .035       0  4974.9    .035       0
  4989.3    .035       0
Bank Sta=4974.9,4989.3
XS Rating Curve= 0 ,0
Exp/Cntr=0.3,0.1

Type RM Length L Ch R = 1 ,29924   ,424,424,424
BEGIN DESCRIPTION:
Stink Creek 58.0
END DESCRIPTION:
XS GIS Cut Line= 3
      1440410.83      6861680.61       1441097.5      6861791.13
      1442570.53      6861723.03
#Sta/Elev= 30
  4304.5 2017.29  4373.9 2015.83  4470.8 2013.87  4512.3 2012.14  4551.8 2011.95
  4606.5 2009.71    4735 2006.42  4794.9 2005.71  4821.6 2002.21  4826.7 2002.64
  4865.8  1999.8  4875.9 2000.58    4957 1999.26  4967.1 2000.18    5000 1997.37
  5000.2 1996.43  5000.7 1995.93  5014.9 1996.43  5017.5 1999.64  5027.5 2005.59
  5037.5 2006.99  5209.8 2008.82  5231.6 2008.93  5393.5 2009.92  5441.5 2010.07
  5688.2 2010.46  5718.3 2011.62  6028.6 2013.02  6238.8  2016.3  6474.6 2021.75
#Mann= 10 ,-1 , 0
  4304.5     .07       0  4373.9    .035       0  4606.5     .07       0
    4735     .16       0  5000.2     .07       0  5014.9     .16       0
  5209.8     .16       0  5231.6     .07       0  5393.5     .16       0
  5441.5     .07       0
Bank Sta=5000.2,5014.9
XS Rating Curve= 0 ,0
Exp/Cntr=0.3,0.1

Type RM Length L Ch R = 1 ,29500   ,321,321,321
BEGIN DESCRIPTION:
Stink Creek 57.0
END DESCRIPTION:
XS GIS Cut Line= 3
      1440482.37      6862153.13      1440955.04      6862158.66
      1441904.96      6862337.99
#Sta/Elev= 30
  4527.3 2012.38  4629.9 2012.93  4709.9  2010.9  4789.9 2006.27  4905.7 2003.61
    4960 2000.36    4980 2001.62    4990 1999.14  4997.5 1994.31  5002.5 1994.31
  5002.8 1991.69  5003.3 1991.19  5017.5 1991.69  5019.3 1993.97  5024.4 1994.05
  5030.5 1997.42  5081.5 2003.68  5122.1 2003.18  5401.3 2005.12  5511.2 2003.36
  5578.9 2003.55  5621.1 2003.69  5641.1 2006.06  5661.4 2006.11    5753 2012.64
  5830.7 2013.12  5844.6 2013.97  5883.1  2013.4  5944.2 2014.09  5966.7 2014.13
#Mann= 7 ,-1 , 0
  4527.3     .07       0  4905.7     .16       0  5002.8     .07       0
  5017.5     .16       0  5081.5     .07       0  5578.9     .16       0
  5944.2     .07       0
Bank Sta=5002.8,5017.5
XS Rating Curve= 0 ,0
Exp/Cntr=0.3,0.1

Type RM Length L Ch R = 1 ,29179   ,882,882,882
BEGIN DESCRIPTION:
Stink Creek 56.0
END DESCRIPTION:
XS GIS Cut Line= 3
      1439596.09      6862480.89      1440904.68      6862463.29
      1441805.02        6862438.
#Sta/Elev= 30
  3691.3 2010.27  3740.2 2005.29  3782.4 2004.44    3971 2003.22  4150.2 2002.23
  4330.3 2003.15  4390.3 2005.06  4530.3 2006.14  4920.3 2003.33  4950.3    2001
  4960.3 1999.06  4970.3 1994.88    4973 1990.02  4973.5 1989.52  4987.7 1990.02
  4990.3 1992.45  4997.7 1994.81  5047.9 1998.23  5070.4 2000.03  5140.4 2001.44
  5200.4 2000.67  5245.3 2001.92  5590.6 2001.84  5620.6 2002.18  5630.6 2003.43
  5670.6 2003.11  5691.7 2004.79  5831.1 2012.64  5870.7 2015.87  5900.7 2015.65
#Mann= 9 ,-1 , 0
  3691.3     .07       0  3782.4    .035       0    3971     .07       0
    4973     .07       0  4987.7     .07       0  5047.9     .16       0
  5245.3     .07       0  5691.7     .16       0  5831.1     .07       0
Bank Sta=4973,4987.7
XS Rating Curve= 0 ,0
Exp/Cntr=0.3,0.1

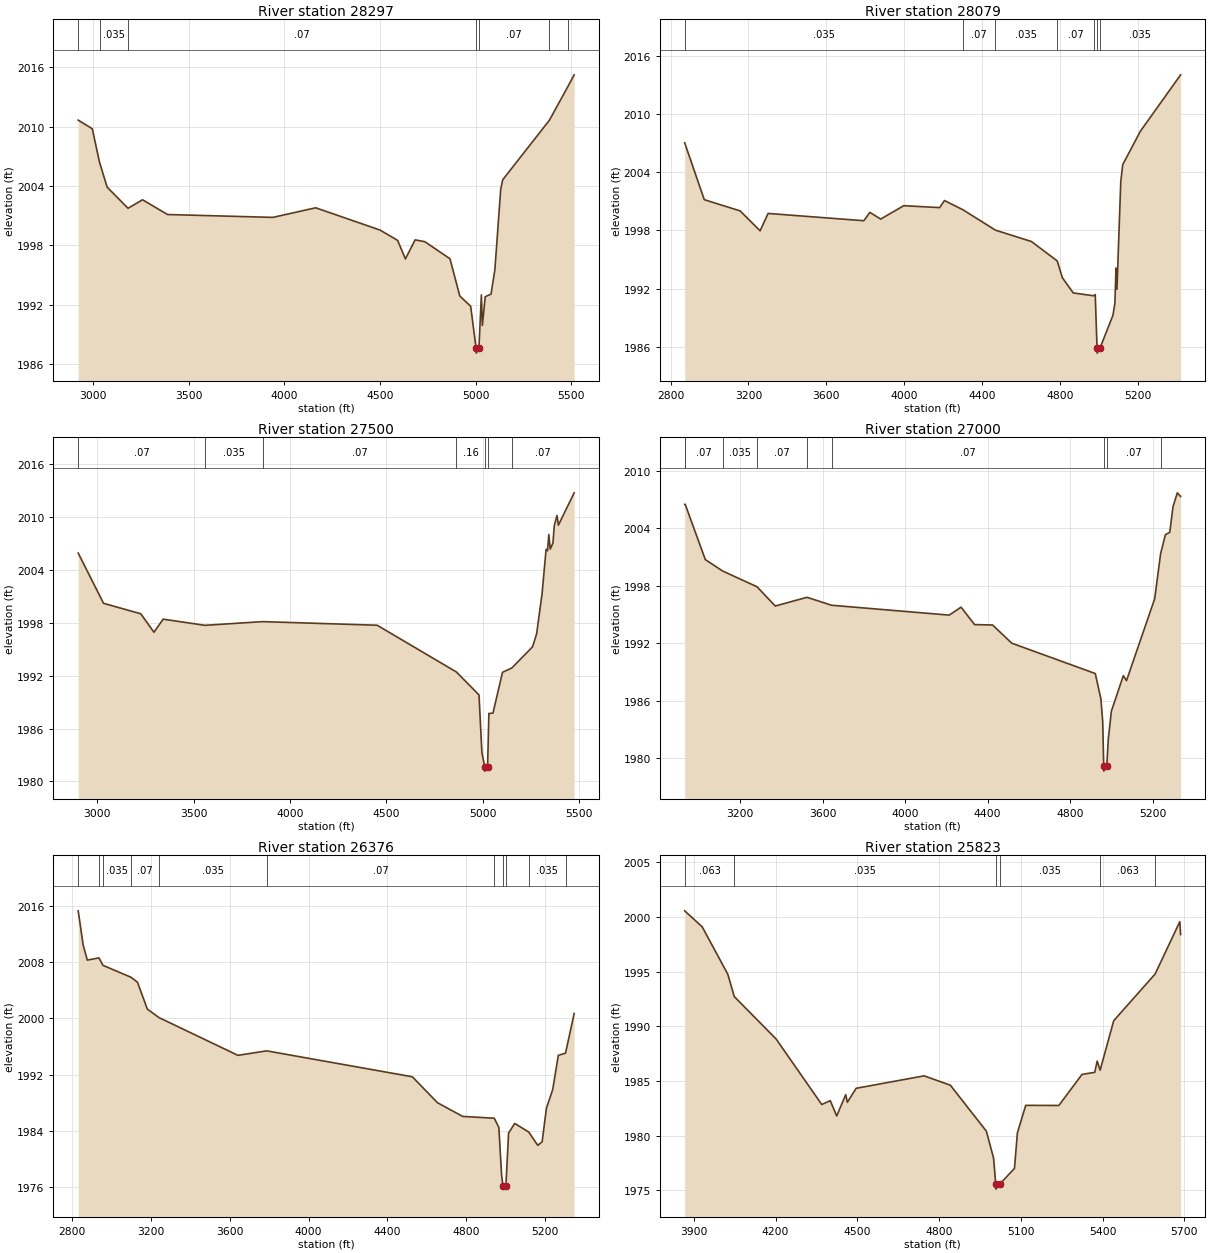
Type RM Length L Ch R = 1 ,28297   ,218,218,218
BEGIN DESCRIPTION:
Stink Creek 55.0
END DESCRIPTION:
XS GIS Cut Line= 3
      1439506.67       6862529.1      1441545.01        6862928.
        1442055.      6863001.03
#Sta/Elev= 30
    2923 2010.65  2996.5 2009.78  3034.4  2006.4  3074.1 2003.88  3183.4 2001.74
  3259.2  2002.6    3390 2001.11  3940.3 2000.82  4164.4 2001.79  4500.5 1999.54
  4592.4  1998.5  4633.2 1996.62  4684.1 1998.55  4735.1 1998.36  4866.1 1996.64
  4917.6 1992.87  4974.3 1991.84  5002.7  1987.6  5003.2  1987.1  5017.5  1987.6
  5030.3 1992.98  5035.3  1989.9  5050.5  1992.8  5080.8 1993.07  5100.9 1995.55
  5131.3 2003.64  5141.4 2004.61  5385.8 2010.64  5485.4 2014.15  5515.2 2015.23
#Mann= 7 ,-1 , 0
    2923     .07       0  3034.4    .035       0  3183.4     .07       0
  5002.7     .07       0  5017.5     .07       0  5385.8    .035       0
  5485.4     .07       0
Bank Sta=5002.7,5017.5
XS Rating Curve= 0 ,0
Exp/Cntr=0.3,0.1

Type RM Length L Ch R = 1 ,28079   ,579,579,579
BEGIN DESCRIPTION:
Stink Creek 54.0
END DESCRIPTION:
XS GIS Cut Line= 3
      1439576.81      6862647.43      1441654.67      6863103.42
      1442070.21      6863149.61
#Sta/Elev= 30
  2872.7 2007.03  2973.2 2001.17  3157.5 2000.01  3259.9 1997.96  3300.8 1999.75
  3792.3    1999    3823 1999.86  3878.8 1999.17    3997 2000.55  4181.3 2000.35
  4205.9 2001.08  4300.8 2000.13  4467.7 1998.03  4652.2 1996.86  4784.8 1994.86
  4811.2 1993.13  4867.2 1991.56  4971.3 1991.27  4979.9 1991.39  4989.2 1985.86
  4989.7 1985.36    5004 1985.86  5070.8 1989.26  5080.8  1990.5  5086.3 1994.13
  5091.3 1991.94    5111 2003.05  5121.1 2004.78  5211.6 2008.22  5418.1 2014.03
#Mann= 7 ,-1 , 0
  2872.7    .035       0  4300.8     .07       0  4467.7    .035       0
  4784.8     .07       0  4971.3    .035       0  4989.2    .035       0
    5004    .035       0
Bank Sta=4989.2,5004
XS Rating Curve= 0 ,0
Exp/Cntr=0.3,0.1

Type RM Length L Ch R = 1 ,27500   ,500,500,500
BEGIN DESCRIPTION:
Stink Creek 53.0
END DESCRIPTION:
XS GIS Cut Line= 3
      1439564.53      6862704.76      1441506.18      6863500.29
      1441851.27      6863827.27
#Sta/Elev= 30
  2901.7 2005.92  3033.1 2000.22  3226.4 1999.03  3294.7 1996.94  3342.7 1998.42
  3559.1 1997.72  3859.4 1998.14  4453.1 1997.73    4864 1992.43  4981.6 1989.82
  4996.7 1983.27  5011.3 1981.67  5011.8 1981.17  5026.2 1981.67  5032.9 1987.72
    5054 1987.75  5103.7 1992.39  5152.1 1992.88  5259.4 1995.28  5280.5 1996.74
  5308.8 2001.29  5329.8 2006.34  5337.1 2006.18    5344 2008.03  5351.3 2006.37
  5365.4 2007.07  5372.3 2009.03  5386.5 2010.19  5393.7 2009.09  5475.4 2012.76
#Mann= 7 ,-1 , 0
  2901.7     .07       0  3559.1    .035       0  3859.4     .07       0
    4864     .16       0  5011.3     .07       0  5026.2     .16       0
  5152.1     .07       0
Bank Sta=5011.3,5026.2
XS Rating Curve= 0 ,0
Exp/Cntr=0.3,0.1

Type RM Length L Ch R = 1 ,27000   ,624,624,624
BEGIN DESCRIPTION:
Stink Creek 52.0
END DESCRIPTION:
XS GIS Cut Line= 3
      1439523.48      6862749.62      1441239.92      6863903.08
      1441524.08      6864081.06
#Sta/Elev= 30
    2932 2006.52  2934.5 2006.52    3032 2000.75  3115.6 1999.56  3282.7 1997.91
    3371  1995.9  3524.7 1996.81    3644 1995.98    4214 1994.95  4271.2 1995.78
    4337 1993.96    4424 1993.92    4517 1992.02  4921.8 1988.85    4949  1986.2
  4957.9 1983.81  4962.6 1979.16  4963.1 1978.66  4977.5 1979.16    4985 1982.05
  4999.9 1984.93  5057.7 1988.63  5073.1 1988.11  5209.8 1996.67  5238.3 2001.36
  5261.6 2003.35  5282.9  2003.6  5298.2 2006.25  5319.4 2007.72  5335.3 2007.34
#Mann= 9 ,-1 , 0
    2932    .035       0  2934.5     .07       0  3115.6    .035       0
  3282.7     .07       0  3524.7    .035       0    3644     .07       0
  4962.6     .07       0  4977.5     .07       0  5238.3    .035       0
Bank Sta=4962.6,4977.5
XS Rating Curve= 0 ,0
Exp/Cntr=0.3,0.1

Type RM Length L Ch R = 1 ,26376   ,553,553,553
BEGIN DESCRIPTION:
Stink Creek 51.0
END DESCRIPTION:
XS GIS Cut Line= 3
      1439308.26       6862599.5      1440784.95      6864187.65
      1441091.03       6864350.7
#Sta/Elev= 30
  2831.4  2015.3  2856.6 2010.42  2877.6 2008.29  2936.5  2008.6  2957.1 2007.54
  3098.8 2005.85  3132.1 2005.13    3182 2001.31  3242.1 2000.09  3641.7 1994.73
  3787.2 1995.37  4526.1 1991.68  4653.6 1987.99  4781.2 1986.04  4941.7 1985.78
  4964.9 1984.46    4979  1977.6  4985.7 1976.19  4986.2 1975.69  5000.7 1976.19
  5014.2 1983.67  5045.4 1985.04  5116.6 1983.81  5162.3 1981.92  5184.3 1982.42
  5206.2  1987.2    5238 1989.86  5266.5 1994.73    5303 1995.04  5346.8 2000.68
#Mann= 11 ,-1 , 0
  2831.4    .035       0  2936.5     .07       0  2957.1    .035       0
  3098.8     .07       0  3242.1    .035       0  3787.2     .07       0
  4941.7     .16       0  4985.7     .07       0  5000.7     .16       0
  5116.6    .035       0    5303    .063       0
Bank Sta=4985.7,5000.7
XS Rating Curve= 0 ,0
Exp/Cntr=0.3,0.1

Type RM Length L Ch R = 1 ,25823   ,323,323,323
BEGIN DESCRIPTION:
Stink Creek 50.0
END DESCRIPTION:
XS GIS Cut Line= 3
      1439423.43      6864862.98      1440508.77      6864536.43
      1441185.63        6864423.
#Sta/Elev= 30
  3866.6 2000.56  3930.8  1999.1  4024.9 1994.76  4048.6 1992.72  4202.4 1988.83
  4369.5 1982.85  4400.8  1983.2  4424.4  1981.8  4457.4 1983.75  4463.5 1983.05
  4495.7 1984.33  4745.4 1985.47  4841.5 1984.61  4973.6 1980.41    5000 1977.94
  5007.9 1975.61  5008.4 1975.11  5024.3 1975.61  5076.7 1977.01  5087.4 1980.25
  5117.9 1982.77  5239.5 1982.76  5324.5  1985.6  5371.3 1985.79  5380.1 1986.82
    5391 1985.99  5440.8 1990.51  5592.7 1994.78  5683.4 1999.57  5686.3 1998.39
#Mann= 6 ,-1 , 0
  3866.6    .063       0  4048.6    .035       0  5007.9    .035       0
  5024.3    .035       0    5391    .063       0  5592.7    .094       0
Bank Sta=5007.9,5024.3
XS Rating Curve= 0 ,0
Exp/Cntr=0.3,0.1

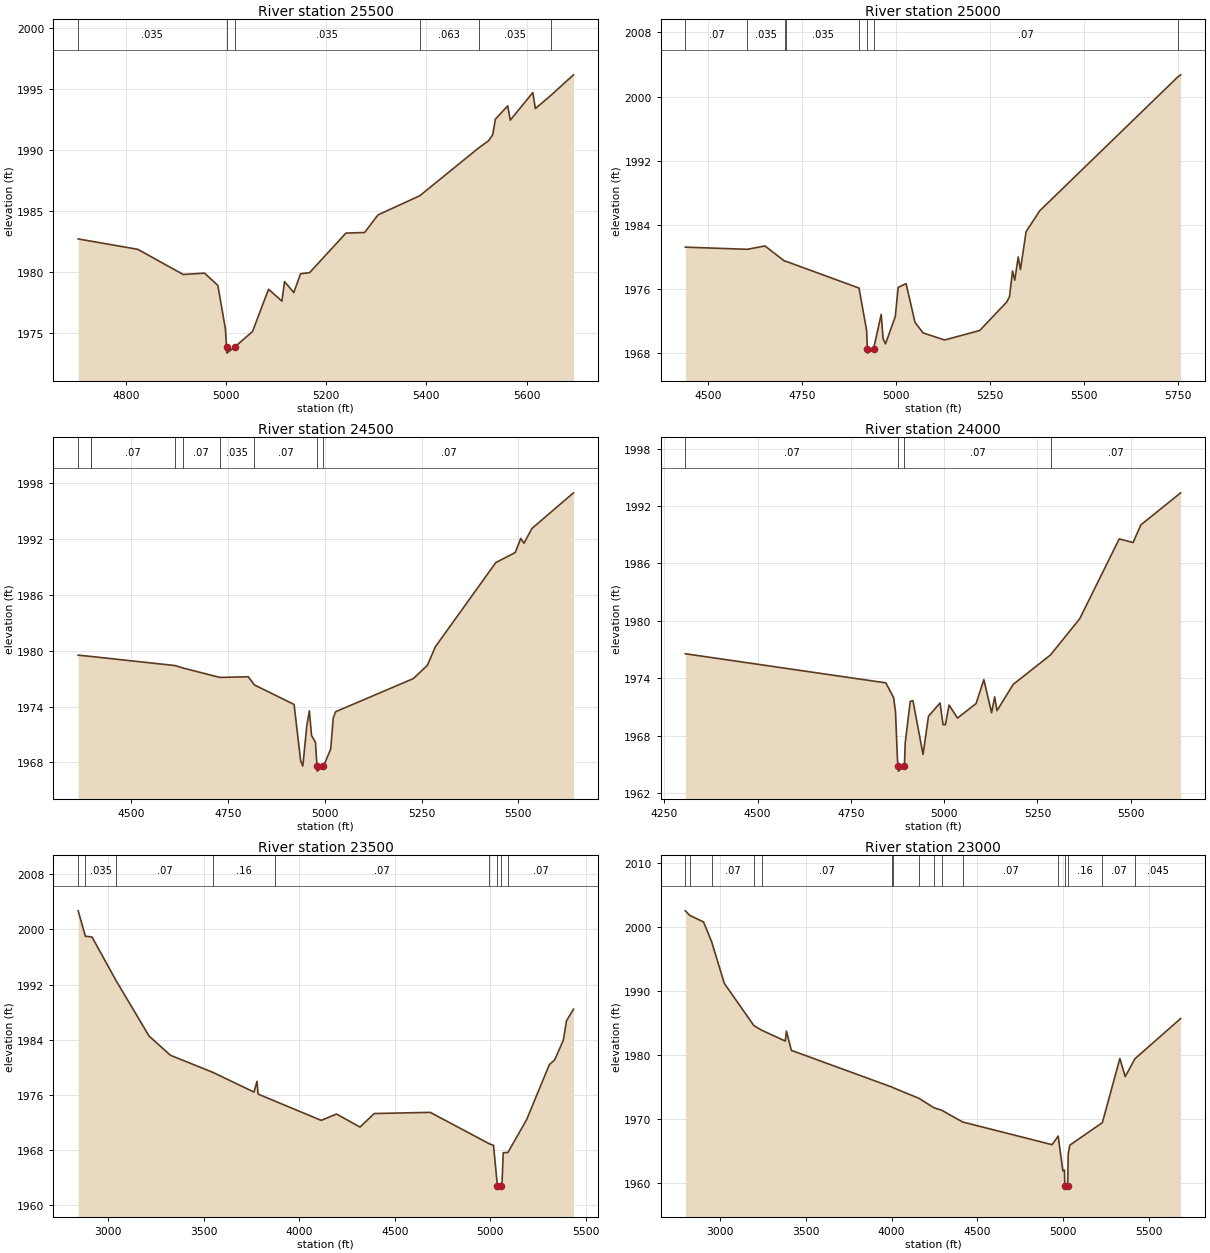
Type RM Length L Ch R = 1 ,25500   ,500,500,500
BEGIN DESCRIPTION:
Stink Creek 49.0
END DESCRIPTION:
XS GIS Cut Line= 3
      1440325.37      6864919.28      1441126.82      6864659.45
      1441270.42       6864689.4
#Sta/Elev= 30
  4704.5 1982.69  4823.6 1981.84  4914.3 1979.78  4956.8 1979.89  4983.5 1978.88
  4998.5 1975.33  5000.8 1973.84  5001.3 1973.34  5017.2 1973.84  5052.7 1975.11
  5084.7 1978.57  5111.4  1977.6  5116.7  1979.2  5135.1  1978.3  5148.6 1979.84
  5166.7 1979.93  5239.3 1983.17  5276.6 1983.22  5303.3 1984.66  5386.8 1986.23
  5504.8 1990.16  5524.1 1990.73  5532.4 1991.23  5537.7  1992.5  5562.4 1993.59
  5567.5 1992.42  5612.5 1994.68  5617.6 1993.37  5648.1 1994.43  5693.7 1996.13
#Mann= 6 ,-1 , 0
  4704.5    .035       0  5000.8    .035       0  5017.2    .035       0
  5386.8    .063       0  5504.8    .035       0  5648.1     .07       0
Bank Sta=5000.8,5017.2
XS Rating Curve= 0 ,0
Exp/Cntr=0.3,0.1

Type RM Length L Ch R = 1 ,25000   ,500,500,500
BEGIN DESCRIPTION:
Stink Creek 48.0
END DESCRIPTION:
XS GIS Cut Line= 3
      1440313.59      6865171.54      1440872.09      6865205.09
      1441505.01      6864787.99
#Sta/Elev= 30
  4440.5 1981.23  4605.4 1980.96  4652.3 1981.38  4704.4 1979.49  4708.4 1979.46
  4902.4 1976.13  4922.8 1970.83  4924.6 1968.52  4925.1 1968.02    4941 1968.52
  4961.5 1972.85  4966.5 1969.82  4972.9 1969.18    4999 1972.58  5006.6 1976.22
  5027.7 1976.68  5051.4 1971.85  5072.9 1970.54  5130.1 1969.66  5223.5 1970.84
  5295.7 1974.41  5302.9 1975.09  5310.8 1978.26  5316.8 1977.11  5325.9 1980.01
  5331.9 1978.43  5346.9 1983.16  5383.1 1985.76  5749.8 2002.42    5758 2002.71
#Mann= 8 ,-1 , 0
  4440.5     .07       0  4605.4    .035       0  4704.4     .07       0
  4708.4    .035       0  4902.4     .07       0  4924.6     .07       0
    4941     .07       0  5749.8    .035       0
Bank Sta=4924.6,4941
XS Rating Curve= 0 ,0
Exp/Cntr=0.3,0.1

Type RM Length L Ch R = 1 ,24500   ,500,500,500
BEGIN DESCRIPTION:
Stink Creek 47.0
END DESCRIPTION:
XS GIS Cut Line= 3
      1440543.89      6865270.65      1441116.87      6865550.09
      1441505.02      6865037.97
#Sta/Elev= 30
  4362.5 1979.52  4396.1 1979.38  4396.2 1979.38  4613.5  1978.4  4632.7 1978.15
  4728.7 1977.13  4802.3  1977.2  4818.1 1976.32  4920.5 1974.23  4937.5 1968.18
    4943 1967.61  4953.4 1971.95    4960 1973.54  4965.6 1970.91  4975.7 1970.16
  4979.8 1967.57  4980.3 1967.07  4996.3 1967.57  5015.2 1969.45  5021.6 1972.76
  5027.9 1973.45  5228.5    1977    5265 1978.43  5285.8 1980.43  5441.8 1989.46
    5492 1990.54  5506.3 1992.05  5514.6 1991.54  5535.4 1993.13  5642.6 1996.95
#Mann= 9 ,-1 , 0
  4362.5     .07       0  4396.1    .035       0  4396.2     .07       0
  4613.5    .035       0  4632.7     .07       0  4728.7    .035       0
  4818.1     .07       0  4979.8     .07       0  4996.3     .07       0
Bank Sta=4979.8,4996.3
XS Rating Curve= 0 ,0
Exp/Cntr=0.3,0.1

Type RM Length L Ch R = 1 ,24000   ,500,500,500
BEGIN DESCRIPTION:
Stink Creek 46.0
END DESCRIPTION:
XS GIS Cut Line= 4
      1440862.51      6865639.47      1441048.43      6866012.15
      1441315.71      6865938.21      1441704.97      6865438.03
#Sta/Elev= 30
  4306.2 1976.57  4843.6 1973.53  4864.4 1971.99  4869.5 1970.52  4874.8 1965.48
  4876.9 1964.81  4877.4 1964.31  4893.4 1964.81  4895.5 1967.25    4909 1971.59
  4916.3 1971.66  4943.4 1966.05  4957.8 1970.04  4988.9 1971.43    4997 1969.16
  5003.3 1969.16  5013.1 1971.21  5035.7 1969.85  5085.5 1971.37  5106.3 1973.86
  5127.1 1970.41  5135.3 1972.07  5141.6 1970.63    5185 1973.37  5285.1 1976.45
  5363.3 1980.23  5469.2 1988.57  5506.3 1988.19  5527.1 1990.03  5633.8 1993.38
#Mann= 4 ,-1 , 0
  4306.2     .07       0  4876.9     .07       0  4893.4     .07       0
  5285.1     .07       0
Bank Sta=4876.9,4893.4
XS Rating Curve= 0 ,0
Exp/Cntr=0.3,0.1

Type RM Length L Ch R = 1 ,23500   ,500,500,500
BEGIN DESCRIPTION:
Stink Creek 45.0
END DESCRIPTION:
XS GIS Cut Line= 3
        1439455.        6865188.      1441314.48      6866280.17
      1441704.96      6866088.02
#Sta/Elev= 30
  2843.5 2002.69  2881.1 1999.01  2915.7  1998.9  3041.1 1992.61  3214.6 1984.53
    3326 1981.75  3547.4 1979.28  3763.6 1976.41  3779.2 1977.97    3785 1976.12
  3871.4 1975.12  4115.2 1972.31  4195.3 1973.23  4318.3 1971.34  4392.6  1973.3
  4685.7 1973.47  4995.2 1968.91  5016.8 1968.69  5036.9 1962.84  5037.4 1962.34
  5053.4 1962.84  5061.7 1963.45  5067.5 1967.62  5092.3 1967.66  5190.1 1972.42
  5308.9 1980.39  5336.9 1981.08  5381.9 1983.93  5398.8 1986.76  5435.2 1988.43
#Mann= 9 ,-1 , 0
  2843.5    .063       0  2881.1    .035       0  3041.1     .07       0
  3547.4     .16       0  3871.4     .07       0  4995.2     .16       0
  5036.9     .07       0  5053.4     .16       0  5092.3     .07       0
Bank Sta=5036.9,5053.4
XS Rating Curve= 0 ,0
Exp/Cntr=0.3,0.1

Type RM Length L Ch R = 1 ,23000   ,500,500,500
BEGIN DESCRIPTION:
Stink Creek 44.0
END DESCRIPTION:
XS GIS Cut Line= 3
      1439405.02      6865238.01      1441098.49       6866646.1
      1441755.02      6866838.01
#Sta/Elev= 30
  2797.6 2002.49    2822  2001.8  2903.7 2000.75  2950.7 1997.67  3024.8 1991.14
  3196.9 1984.55    3242 1983.83  3380.2 1982.12  3386.7 1983.67  3415.4 1980.67
  4000.3 1974.94  4007.7 1974.84  4158.9 1973.17  4247.6 1971.68  4290.7 1971.32
  4413.2 1969.47  4934.8 1965.92  4970.3 1967.27  4997.6 1961.82  5006.8 1961.96
  5008.9 1959.47  5009.4 1958.97  5025.5 1959.47  5028.7 1964.47    5038 1965.84
  5227.7 1969.37  5329.8  1979.4    5361 1976.56  5417.4 1979.35    5684 1985.65
#Mann= 16 ,-1 , 0
  2797.6    .063       0    2822    .035       0  2950.7     .07       0
  3196.9     .16       0    3242     .07       0  4000.3    .035       0
  4007.7     .07       0  4158.9    .035       0  4247.6     .07       0
  4290.7    .035       0  4413.2     .07       0  4970.3     .16       0
  5008.9     .07       0  5025.5     .16       0  5227.7     .07       0
  5417.4    .045       0
Bank Sta=5008.9,5025.5
XS Rating Curve= 0 ,0
Exp/Cntr=0.3,0.1