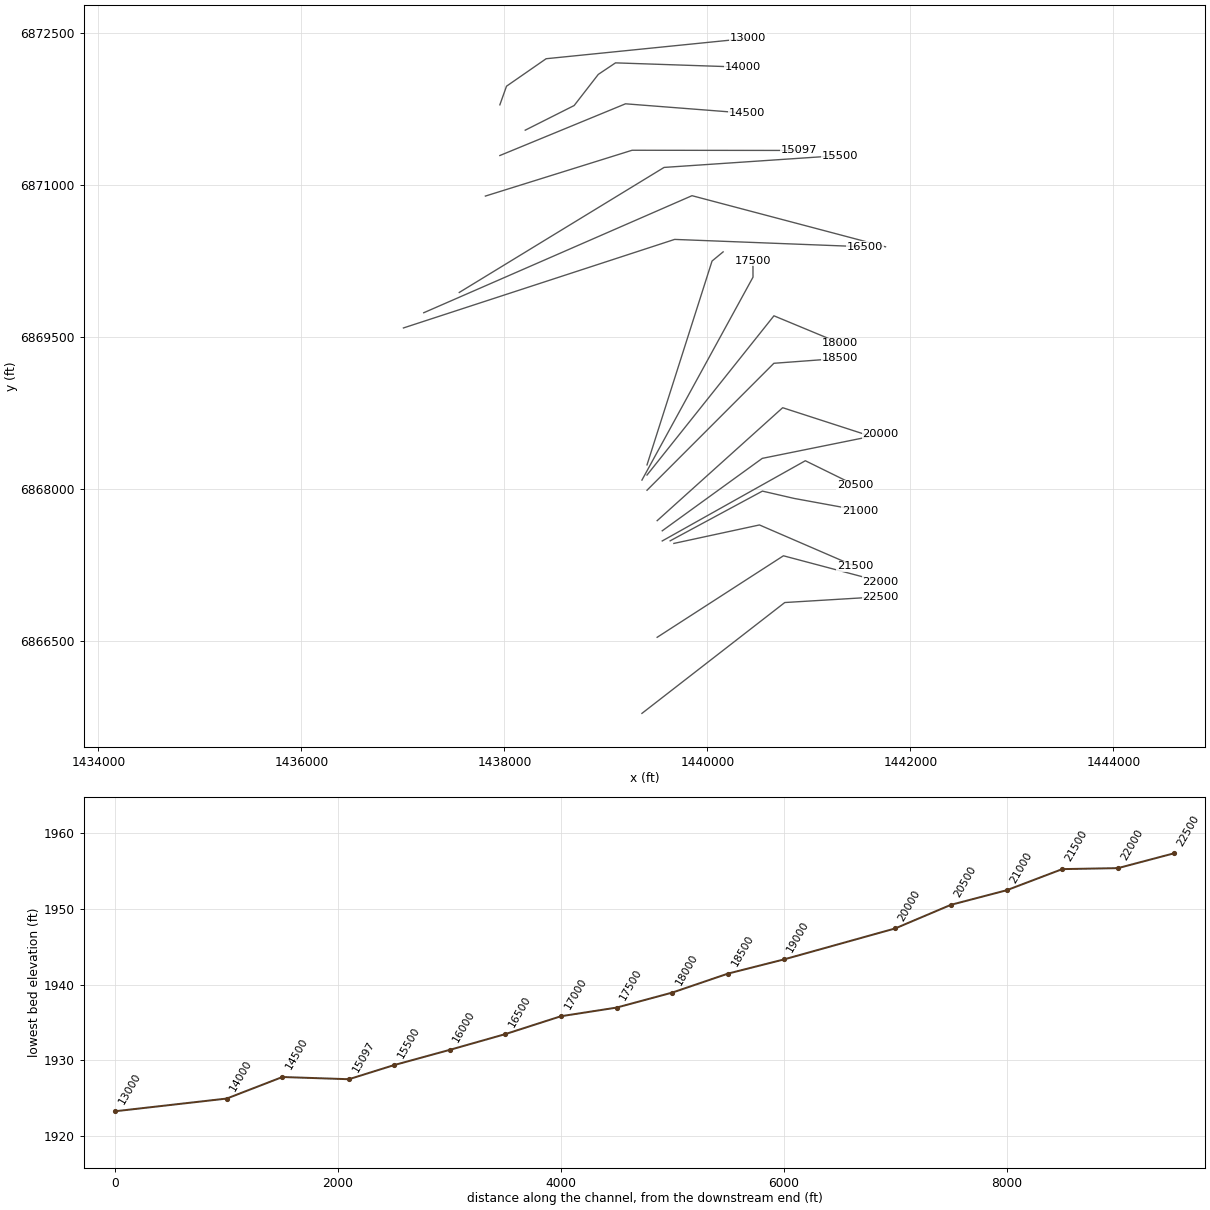
HEC-RAS study Stink Creek.prj: Stink Creek Base Level Engineering

--- Stink Creek.g01 (geometry) --- (continued)

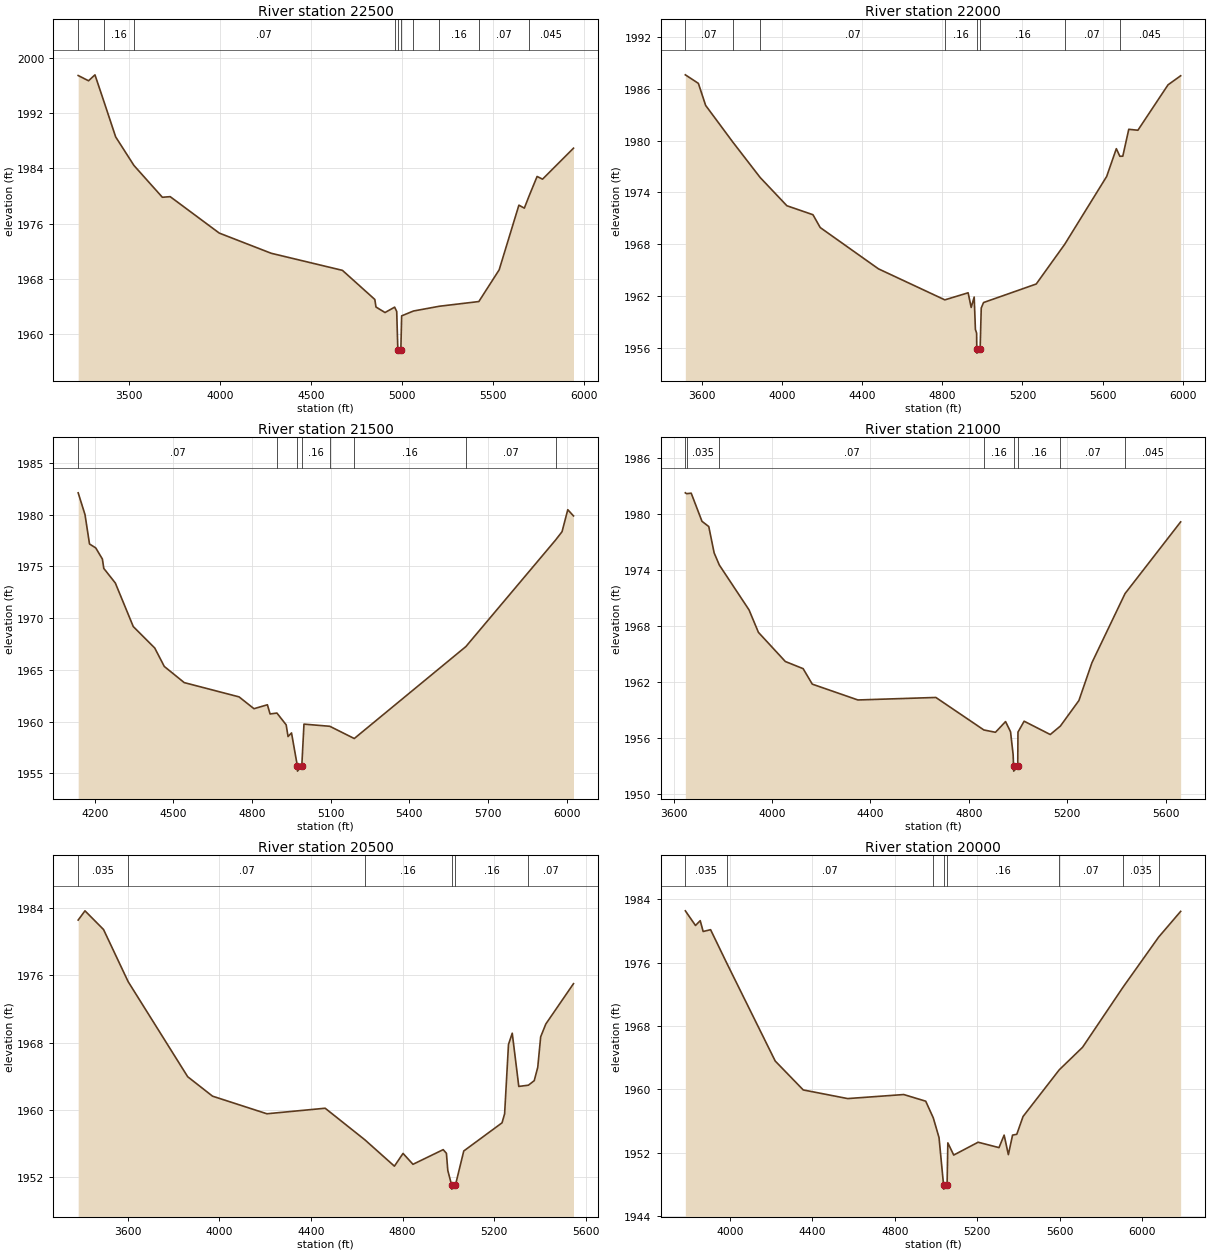
Type RM Length L Ch R = 1 ,22500   ,500,500,500
BEGIN DESCRIPTION:
Stink Creek 43.0
END DESCRIPTION:
XS GIS Cut Line= 3
      1439354.96      6865787.97      1440762.29      6866880.79
      1441704.96        6866938.
#Sta/Elev= 30
  3218.2 1997.44  3275.3 1996.68  3310.6 1997.54  3361.7 1993.54  3424.6 1988.56
  3525.2 1984.43  3681.6 1979.83  3724.7 1979.92  3994.8 1974.65  4280.8 1971.73
  4672.7 1969.26    4851 1965.05  4857.3 1963.96  4907.1 1963.16    4960 1963.94
  4971.4 1963.31  4977.6 1957.79  4978.1 1957.29  4994.2 1957.79  4998.5 1962.68
  5063.4 1963.38  5206.1 1964.07  5423.4 1964.75  5535.2 1969.33  5643.9 1978.69
  5673.9 1978.26  5698.5 1979.92  5744.1 1982.84  5774.1 1982.45  5944.4 1986.93
#Mann= 10 ,-1 , 0
  3218.2    .035       0  3361.7     .16       0  3525.2     .07       0
    4960     .16       0  4977.6     .07       0  4994.2     .16       0
  5063.4     .07       0  5206.1     .16       0  5423.4     .07       0
  5698.5    .045       0
Bank Sta=4977.6,4994.2
XS Rating Curve= 0 ,0
Exp/Cntr=0.3,0.1

Type RM Length L Ch R = 1 ,22000   ,500,500,500
BEGIN DESCRIPTION:
Stink Creek 42.0
END DESCRIPTION:
XS GIS Cut Line= 3
      1439504.97      6866537.98      1440749.08      6867341.63
      1441705.01        6867088.
#Sta/Elev= 30
  3518.9 1987.64  3583.9 1986.65  3620.2 1984.09  3755.9 1979.83  3891.6 1975.74
  4025.3 1972.45  4155.3 1971.41  4191.6 1969.92  4481.9 1965.13    4813 1961.53
  4929.2 1962.35  4944.4 1960.65  4959.4 1961.86  4965.5 1958.09  4971.5 1957.67
  4972.3 1955.85  4972.8 1955.35  4989.1 1955.85  4994.6 1960.59  5006.1 1961.22
  5268.8 1963.37  5410.9 1967.98  5620.1 1975.85  5668.3 1979.07  5685.9 1978.19
  5700.5  1978.2  5730.3 1981.32  5775.7 1981.21  5926.1 1986.48    5989 1987.53
#Mann= 8 ,-1 , 0
  3518.9     .07       0  3755.9    .035       0  3891.6     .07       0
    4813     .16       0  4972.3     .07       0  4989.1     .16       0
  5410.9     .07       0  5685.9    .045       0
Bank Sta=4972.3,4989.1
XS Rating Curve= 0 ,0
Exp/Cntr=0.3,0.1

Type RM Length L Ch R = 1 ,21500   ,500,500,500
BEGIN DESCRIPTION:
Stink Creek 41.0
END DESCRIPTION:
XS GIS Cut Line= 3
      1439669.52      6867463.52      1440512.87      6867645.69
      1441455.04      6867237.98
#Sta/Elev= 30
  4137.2  1982.1  4163.3 1979.99  4180.4 1977.16  4204.2 1976.78  4229.6  1975.7
  4234.9  1974.8  4278.9 1973.39  4347.4 1969.18  4429.3 1967.11  4465.7 1965.33
  4541.8 1963.77    4751 1962.39  4807.8 1961.25    4859 1961.63  4869.2 1960.74
  4895.3 1960.83  4930.6 1959.69  4937.8 1958.56    4951 1958.91  4973.3 1955.72
  4973.8 1955.22  4990.2 1955.72  4998.5 1959.76  5097.1 1959.55  5190.4 1958.37
  5616.1 1967.25  5958.6 1977.55    5983 1978.35  6004.8 1980.47  6026.6 1979.87
#Mann= 8 ,-1 , 0
  4137.2     .07       0  4895.3     .16       0  4973.3     .07       0
  4990.2     .16       0  5097.1     .07       0  5190.4     .16       0
  5616.1     .07       0  5958.6    .045       0
Bank Sta=4973.3,4990.2
XS Rating Curve= 0 ,0
Exp/Cntr=0.3,0.1

Type RM Length L Ch R = 1 ,21000   ,500,500,500
BEGIN DESCRIPTION:
Stink Creek 40.0
END DESCRIPTION:
XS GIS Cut Line= 4
      1439633.24      6867489.34      1440542.11      6867979.42
       1440854.2      6867907.29      1441504.96      6867788.01
#Sta/Elev= 30
  3647.1 1982.31  3651.9 1982.22    3671 1982.27  3714.8 1979.25  3742.4 1978.69
  3764.3 1975.86  3785.3 1974.56  3906.2 1969.74  3944.3 1967.33  4053.8  1964.2
  4126.3 1963.43  4163.3 1961.77    4349 1960.07    4666 1960.34  4861.2 1956.85
  4908.4  1956.6  4949.5 1957.75  4969.8 1956.65  4980.3 1954.19  4982.1 1952.93
  4982.6 1952.43    4999 1952.93    5000 1956.62    5025 1957.79  5131.3 1956.36
  5172.5 1957.27  5247.8 1960.01  5300.9 1964.08  5435.4 1971.49  5661.6 1979.19
#Mann= 8 ,-1 , 0
  3647.1     .07       0  3651.9    .035       0  3785.3     .07       0
  4861.2     .16       0  4982.1     .07       0    4999     .16       0
  5172.5     .07       0  5435.4    .045       0
Bank Sta=4982.1,4999
XS Rating Curve= 0 ,0
Exp/Cntr=0.3,0.1

Type RM Length L Ch R = 1 ,20500   ,500,500,500
BEGIN DESCRIPTION:
Stink Creek 39.0
END DESCRIPTION:
XS GIS Cut Line= 3
      1439554.99      6867487.99      1440964.96      6868278.79
        1441455.        6868038.
#Sta/Elev= 30
  3383.4 1982.61  3413.1 1983.71  3494.1 1981.48  3601.6 1975.26  3861.5 1963.92
    3970  1961.6  4207.3  1959.5  4461.8 1960.16  4635.3 1956.39  4764.1 1953.25
  4801.8 1954.77  4845.2 1953.47  4977.1 1955.22  4991.2 1954.78  4997.2 1952.74
  5013.8 1951.01  5014.3 1950.51  5030.8 1951.01  5066.9 1955.06    5234 1958.42
  5245.3  1959.5  5262.2 1967.77  5278.6 1969.11  5307.2 1962.76  5349.2 1962.91
  5374.6 1963.45    5390 1965.05  5402.7 1968.68  5425.2 1970.21    5546 1975.02
#Mann= 6 ,-1 , 0
  3383.4    .035       0  3601.6     .07       0  4635.3     .16       0
  5013.8     .07       0  5030.8     .16       0  5349.2     .07       0
Bank Sta=5013.8,5030.8
XS Rating Curve= 0 ,0
Exp/Cntr=0.3,0.1

Type RM Length L Ch R = 1 ,20000   ,1000,1000,1000
BEGIN DESCRIPTION:
Stink Creek 38.0
END DESCRIPTION:
XS GIS Cut Line= 3
      1439554.98      6867587.99      1440540.73      6868302.21
        1441705.        6868538.
#Sta/Elev= 30
  3782.7 1982.53  3832.1 1980.68    3855 1981.29  3869.2 1979.92  3905.3 1980.15
  3984.4  1975.9  4219.2 1963.57  4355.3 1959.92  4571.1 1958.83  4843.3 1959.34
    4950  1958.5  4986.8 1956.39  5014.6 1953.91  5036.7  1947.9  5037.2  1947.4
  5053.7  1947.9  5057.4 1953.24    5086  1951.7  5204.4 1953.32  5305.8 1952.64
  5330.8 1954.22  5351.3 1951.75  5371.7 1954.22  5392.1 1954.32  5422.7 1956.57
  5598.4 1962.46  5711.4  1965.3  5907.8 1972.88  6080.9 1979.21  6187.9 1982.46
#Mann= 8 ,-1 , 0
  3782.7    .035       0  3984.4     .07       0  4986.8     .16       0
  5036.7     .07       0  5053.7     .16       0  5598.4     .07       0
  5907.8    .035       0  6080.9    .045       0
Bank Sta=5036.7,5053.7
XS Rating Curve= 0 ,0
Exp/Cntr=0.3,0.1

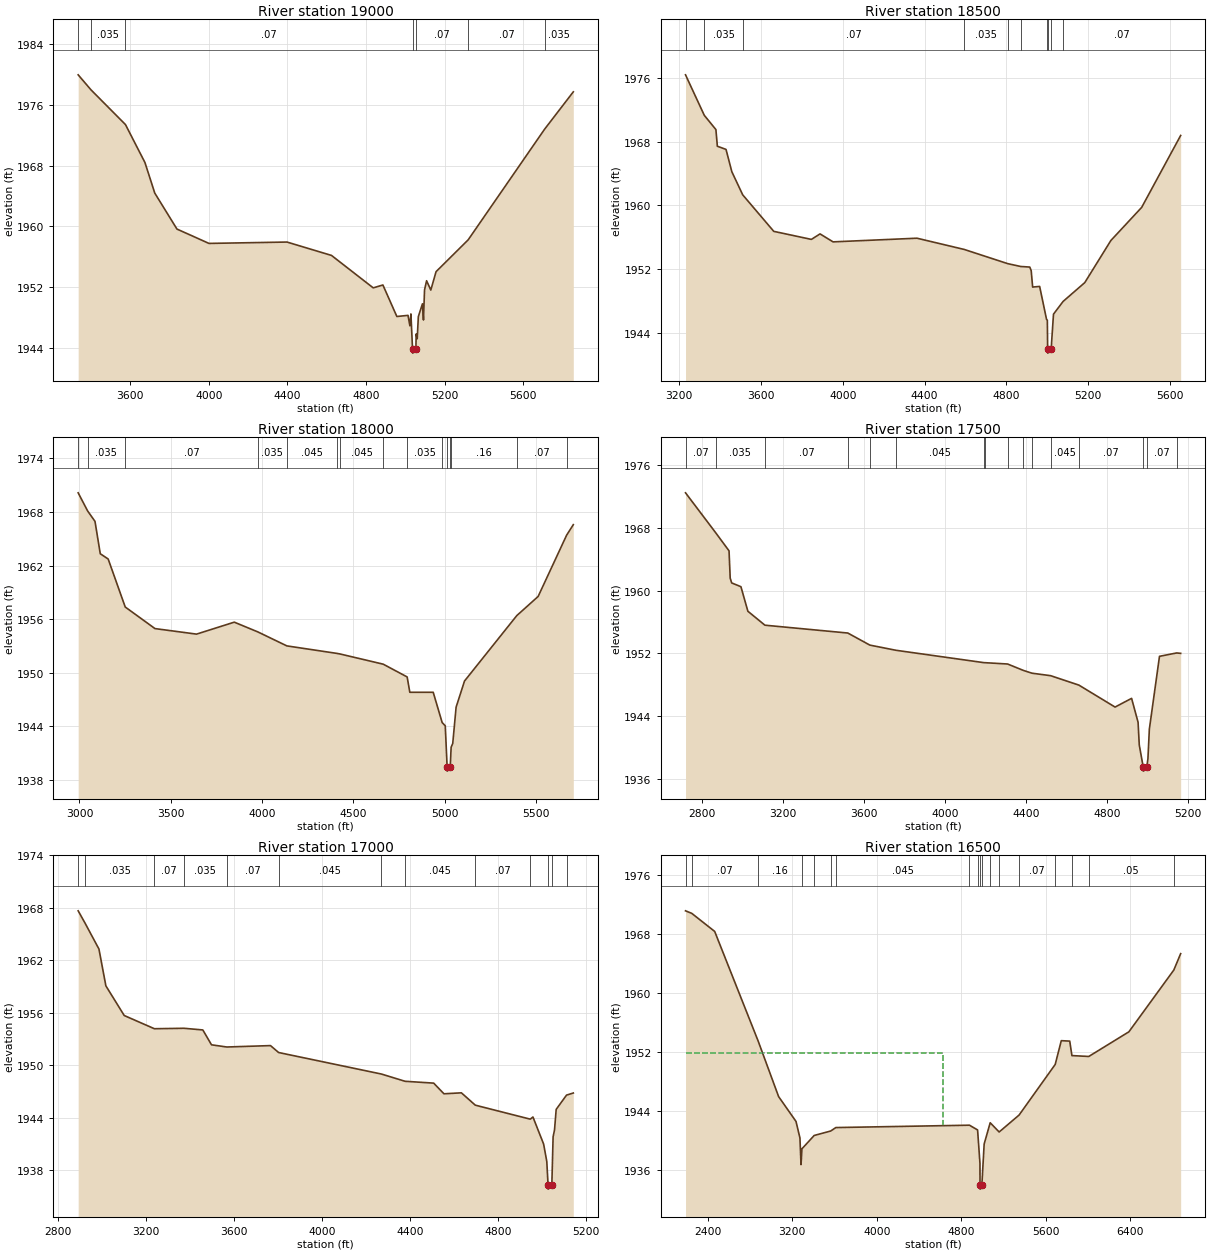
Type RM Length L Ch R = 1 ,19000   ,500,500,500
BEGIN DESCRIPTION:
Stink Creek 37.0
END DESCRIPTION:
XS GIS Cut Line= 3
      1439504.98      6867687.99      1440741.57      6868801.58
      1441555.03      6868537.99
#Sta/Elev= 30
  3335.9 1979.94  3400.9 1977.97  3576.6 1973.39  3675.6  1968.4  3725.7 1964.37
  3838.5 1959.64  4001.5 1957.75  4398.3 1957.93  4624.8 1956.17  4837.1  1951.9
  4886.4 1952.28  4957.4 1948.13  5014.1 1948.28  5023.6 1946.91  5028.9 1948.47
  5037.2 1943.81  5037.7 1943.31  5054.2 1943.81  5055.6 1945.83  5060.9  1945.2
  5066.7 1948.12  5087.6  1949.8  5092.8 1947.67  5098.2 1951.63  5108.7 1952.84
  5130.1 1951.61  5156.8 1954.03  5320.2 1958.22  5709.2 1972.79  5855.1  1977.7
#Mann= 7 ,-1 , 0
  3335.9     .07       0  3400.9    .035       0  3576.6     .07       0
  5037.2     .07       0  5054.2     .07       0  5320.2     .07       0
  5709.2    .035       0
Bank Sta=5037.2,5054.2
XS Rating Curve= 0 ,0
Exp/Cntr=0.3,0.1

Type RM Length L Ch R = 1 ,18500   ,500,500,500
BEGIN DESCRIPTION:
Stink Creek 36.0
END DESCRIPTION:
XS GIS Cut Line= 3
      1439404.98      6867987.98      1440654.98      6869239.58
      1441304.98        6869288.
#Sta/Elev= 30
  3231.1 1976.37  3322.8 1971.29  3379.6  1969.5  3386.7 1967.41  3429.1 1967.01
  3457.4 1964.22  3510.7 1961.31  3662.5 1956.73  3846.3 1955.72  3888.7 1956.41
  3952.4 1955.41  4362.5 1955.87  4593.6 1954.46    4806 1952.68  4869.9 1952.32
    4914 1952.25  4921.1  1951.8  4928.2 1949.74  4962.4 1949.82  4996.1 1945.69
    5000 1945.58  5001.5 1941.95    5002 1941.45  5018.6 1941.95  5030.1 1946.34
  5077.2 1947.94  5183.1  1950.3  5310.6 1955.58  5461.3 1959.74  5651.8 1968.76
#Mann= 10 ,-1 , 0
  3231.1     .07       0  3322.8    .035       0  3510.7     .07       0
  4593.6    .035       0    4806    .045       0  4869.9     .07       0
  4996.1    .035       0  5001.5    .035       0  5018.6    .035       0
  5077.2     .07       0
Bank Sta=5001.5,5018.6
XS Rating Curve= 0 ,0
Exp/Cntr=0.3,0.1

Type RM Length L Ch R = 1 ,18000   ,500,500,500
BEGIN DESCRIPTION:
Stink Creek 35.0
END DESCRIPTION:
XS GIS Cut Line= 3
      1439404.98      6868137.97      1440655.55      6869707.72
      1441304.97      6869438.01
#Sta/Elev= 30
    2993 1970.15  3044.7 1968.12  3085.1 1966.95    3114 1963.32  3157.2 1962.73
  3250.6 1957.35  3413.4 1954.93  3640.9 1954.31  3847.5 1955.65  3976.2 1954.56
  4135.2 1952.99  4408.8 1952.15  4427.2 1952.08  4662.8 1950.94  4793.7 1949.51
  4808.4 1947.79  4936.4 1947.79  4985.3  1944.4  5002.4 1944.03  5012.5 1939.45
    5013 1938.95  5029.6 1939.45  5034.5 1941.63  5043.3 1942.05  5061.7 1946.12
  5107.7 1949.05  5393.6 1956.38  5510.7 1958.53  5666.6  1965.4  5703.2 1966.58
#Mann= 15 ,-1 , 0
    2993     .07       0  3044.7    .035       0  3250.6     .07       0
  3976.2    .035       0  4135.2    .045       0  4408.8     .07       0
  4427.2    .045       0  4662.8     .07       0  4793.7    .035       0
  4985.3     .07       0  5012.5     .07       0  5029.6     .07       0
  5034.5     .16       0  5393.6     .07       0  5666.6    .035       0
Bank Sta=5012.5,5029.6
XS Rating Curve= 0 ,0
Exp/Cntr=0.3,0.1

Type RM Length L Ch R = 1 ,17500   ,500,500,500
BEGIN DESCRIPTION:
Stink Creek 34.0
END DESCRIPTION:
XS GIS Cut Line= 3
      1439355.02      6868088.03      1440449.33      6870088.82
      1440448.81      6870252.52
#Sta/Elev= 30
  2719.5 1972.46  2868.7 1967.36  2934.3 1965.06    2940 1961.58  2947.4 1960.97
    2993 1960.49  3027.3 1957.36  3111.5 1955.58  3520.5 1954.58  3629.6 1953.04
  3758.6 1952.38  4193.4  1950.8  4196.1  1950.8  4309.4 1950.63  4387.6 1949.81
  4429.6 1949.46    4522 1949.14  4661.3 1947.94  4839.9 1945.14  4921.5 1946.25
  4953.5  1943.2  4959.4  1940.3  4979.1 1937.47  4979.6 1936.97  4996.3 1937.47
  5002.1 1938.53  5009.2 1942.33  5059.2 1951.61    5144 1952.04  5163.7 1951.99
#Mann= 16 ,-1 , 0
  2719.5     .07       0  2868.7    .035       0  3111.5     .07       0
  3520.5    .035       0  3629.6     .07       0  3758.6    .045       0
  4193.4     .07       0  4196.1    .045       0  4309.4     .07       0
  4387.6    .045       0  4429.6     .07       0    4522    .045       0
  4661.3     .07       0  4979.1     .07       0  4996.3     .07       0
    5144    .035       0
Bank Sta=4979.1,4996.3
XS Rating Curve= 0 ,0
Exp/Cntr=0.3,0.1

Type RM Length L Ch R = 1 ,17000   ,500,500,500
BEGIN DESCRIPTION:
Stink Creek 33.0
END DESCRIPTION:
XS GIS Cut Line= 3
      1439404.99      6868237.96      1440045.74      6870247.79
      1440155.01      6870338.01
#Sta/Elev= 30
  2890.5 1967.65  2920.8 1966.29    2985 1963.28  3016.5 1959.07  3099.9 1955.68
    3237 1954.17  3371.7 1954.22  3457.3 1954.03  3496.8 1952.33    3566 1952.08
    3765 1952.24  3801.8 1951.45  4269.1 1948.99  4376.9 1948.16  4506.9 1947.95
  4553.6 1946.73  4632.9 1946.84  4696.1 1945.43    4946 1943.83  4958.2 1944.08
  5006.8 1940.98  5021.2 1938.99  5026.9 1936.33  5027.4 1935.83  5044.1 1936.33
  5049.9 1941.82  5056.3 1942.59  5063.9 1944.95    5111 1946.58  5141.7 1946.82
#Mann= 13 ,-1 , 0
  2890.5     .07       0  2920.8    .035       0    3237     .07       0
  3371.7    .035       0    3566     .07       0  3801.8    .045       0
  4269.1     .07       0  4376.9    .045       0  4696.1     .07       0
    4946     .16       0  5026.9     .07       0  5044.1     .16       0
    5111     .07       0
Bank Sta=5026.9,5044.1
XS Rating Curve= 0 ,0
Exp/Cntr=0.3,0.1

Type RM Length L Ch R = 1 ,16500   ,500,500,500
BEGIN DESCRIPTION:
Stink Creek 32.0
END DESCRIPTION:
XS GIS Cut Line= 3
      1437005.01        6869588.      1439677.21      6870461.02
      1441554.99        6870388.
#Sta/Elev= 30
  2188.8 1971.17  2247.5 1970.83    2465 1968.38  2877.1 1953.52  3070.8    1946
  3235.4 1942.64  3272.6  1940.4  3282.9 1936.79  3291.5 1938.93  3407.6 1940.74
  3563.6 1941.34  3612.7 1941.81  4878.4 1942.13  4955.5 1941.49    4978 1936.96
  4978.6 1933.97  4979.1 1933.47  4995.8 1933.97  5017.8 1939.59    5075 1942.46
  5159.8 1941.21  5348.4  1943.5  5690.8 1950.36  5748.4 1953.58  5828.4 1953.52
  5849.1 1951.56  6008.7 1951.44  6388.8 1954.78  6814.5 1963.15  6879.2 1965.37
#Mann= 18 ,-1 , 0
  2188.8    .035       0  2247.5     .07       0  2877.1     .16       0
  3291.5     .07       0  3407.6    .045       0  3563.6     .07       0
  3612.7    .045       0  4878.4     .07       0  4955.5     .16       0
  4978.6     .07       0  4995.8     .16       0    5075     .07       0
  5159.8     .16       0  5348.4     .07       0  5690.8    .035       0
  5849.1     .07       0  6008.7     .05       0  6814.5     .07       0
#XS Ineff= 2 , 0
         4624.37 1951.91
Permanent Ineff=
       F       F
Bank Sta=4978.6,4995.8
XS Rating Curve= 0 ,0
Exp/Cntr=0.3,0.1

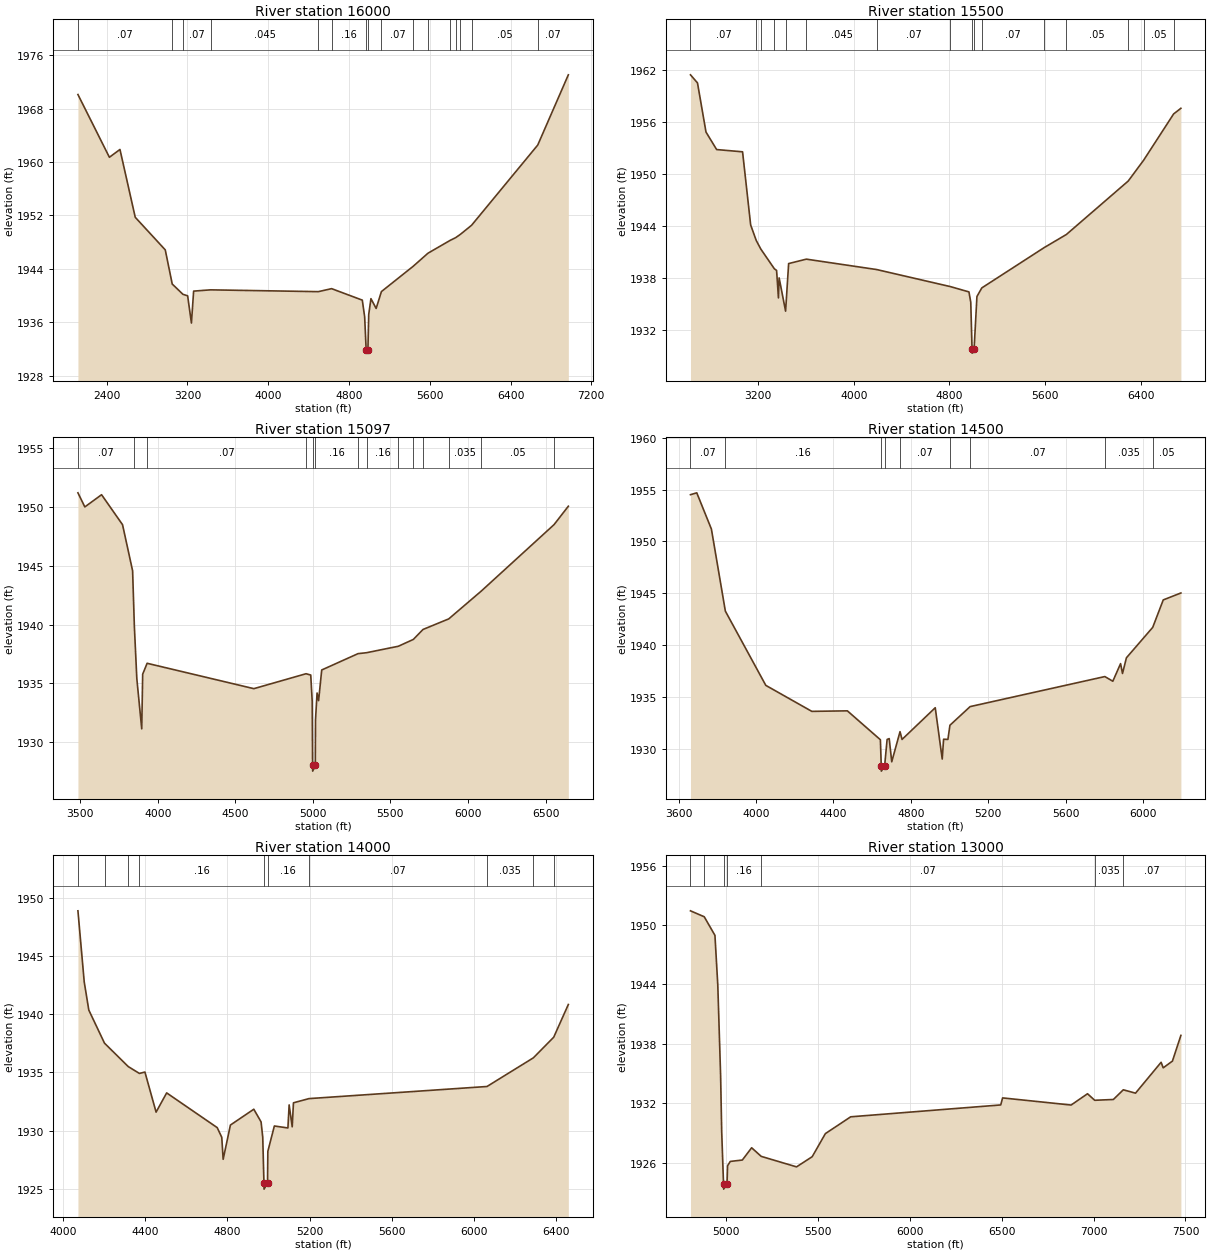
Type RM Length L Ch R = 1 ,16000   ,500,500,500
BEGIN DESCRIPTION:
Stink Creek 31.0
END DESCRIPTION:
XS GIS Cut Line= 3
      1437205.04      6869738.02      1439848.19      6870892.07
      1441754.99        6870388.
#Sta/Elev= 30
  2115.9 1970.09  2427.5  1960.7  2532.1 1961.87  2683.4 1951.72  2980.7 1946.84
  3049.7 1941.73    3156 1940.19  3202.3 1939.97  3239.8 1935.89  3261.6 1940.67
  3429.9 1940.86  4496.6 1940.59  4627.5 1941.04  4931.9 1939.32  4955.3 1936.81
  4970.1 1931.89  4970.6 1931.39  4987.4 1931.89  4995.5 1937.17  5017.4 1939.54
  5069.1 1938.08  5121.1  1940.6  5436.9  1944.4  5581.9 1946.34  5802.6 1948.27
  5856.2 1948.67  5903.5 1949.17  6013.8 1950.52  6669.2 1962.53  6972.3 1973.04
#Mann= 16 ,-1 , 0
  2115.9     .07       0  3049.7     .16       0    3156     .07       0
  3429.9    .045       0  4496.6     .07       0  4627.5     .16       0
  4970.1     .07       0  4987.4     .16       0  5121.1     .07       0
  5436.9    .035       0  5581.9     .05       0  5802.6     .07       0
  5856.2     .05       0  5903.5     .07       0  6013.8     .05       0
  6669.2     .07       0
Bank Sta=4970.1,4987.4
XS Rating Curve= 0 ,0
Exp/Cntr=0.3,0.1

Type RM Length L Ch R = 1 ,15500   ,403,403,403
BEGIN DESCRIPTION:
Stink Creek 30.0
END DESCRIPTION:
XS GIS Cut Line= 3
      1437555.03      6869938.02      1439573.02      6871170.71
      1441304.95        6871288.
#Sta/Elev= 30
  2635.3 1961.48  2693.9 1960.55    2765 1954.88    2854 1952.86  3070.8  1952.6
  3138.5 1944.16  3185.6 1942.36  3223.1 1941.39  3337.1  1939.1  3355.3 1938.92
  3370.7 1935.75  3376.6 1938.06  3430.6 1934.22    3456 1939.71  3603.8 1940.22
    4192 1939.02  4809.2 1937.05  4963.7 1936.44  4978.9 1935.25  4989.6 1929.88
  4990.1 1929.38  5006.9 1929.88  5030.5 1935.91  5071.1  1936.9  5593.7 1941.56
    5778 1943.06  6295.6 1949.23  6424.3 1951.63  6675.3 1956.97  6735.9 1957.62
#Mann= 16 ,-1 , 0
  2635.3     .07       0  3185.6     .16       0  3223.1     .07       0
  3337.1     .16       0  3430.6     .07       0  3603.8    .045       0
    4192     .07       0  4809.2     .16       0  4989.6     .07       0
  5006.9     .16       0  5071.1     .07       0  5593.7    .035       0
    5778     .05       0  6295.6     .07       0  6424.3     .05       0
  6675.3     .07       0
Bank Sta=4989.6,5006.9
XS Rating Curve= 0 ,0
Exp/Cntr=0.3,0.1

Type RM Length L Ch R = 1 ,15097   ,597,597,597
BEGIN DESCRIPTION:
Stink Creek 29.0
END DESCRIPTION:
XS GIS Cut Line= 3
       1437812.4      6870888.22      1439257.94      6871339.99
      1440905.04        6871338.
#Sta/Elev= 30
  3485.5 1951.22    3530 1950.02  3637.9 1951.06    3773 1948.51    3838 1944.58
  3849.3 1939.85  3865.2  1935.4  3896.8 1931.13  3902.9 1935.78  3931.5 1936.71
  4619.7 1934.55  4955.9 1935.82  4986.4 1935.71  4995.8 1933.47  4998.4 1928.03
  4998.9 1927.53  5015.7 1928.03  5017.1 1931.87  5027.1 1934.18  5037.1 1933.53
  5057.1 1936.14  5291.1 1937.53  5346.2 1937.61  5551.3 1938.16  5647.8 1938.74
  5710.3 1939.59  5876.1 1940.49  6085.2 1942.85  6554.7 1948.51  6647.1 1950.08
#Mann= 14 ,-1 , 0
  3485.5     .07       0  3849.3     .16       0  3931.5     .07       0
  4955.9     .16       0  4998.4     .07       0  5015.7     .16       0
  5291.1     .07       0  5346.2     .16       0  5551.3     .07       0
  5647.8     .16       0  5710.3     .07       0  5876.1    .035       0
  6085.2     .05       0  6554.7     .07       0
Bank Sta=4998.4,5015.7
XS Rating Curve= 0 ,0
Exp/Cntr=0.3,0.1

Type RM Length L Ch R = 1 ,14500   ,500,500,500
BEGIN DESCRIPTION:
Stink Creek 28.0
END DESCRIPTION:
XS GIS Cut Line= 3
      1437954.98      6871287.99      1439193.19      6871797.93
      1440385.89      6871705.18
#Sta/Elev= 30
  3660.9 1954.51  3693.4 1954.69  3769.1 1951.19  3841.2 1943.27  4050.3  1936.1
  4288.2 1933.59    4472 1933.64  4642.7 1930.85  4647.2 1928.32  4647.7 1927.82
  4664.5 1928.32  4677.5 1930.88  4688.3 1930.96  4701.4 1928.72  4744.2 1931.63
  4754.7 1930.88  4926.3 1933.94  4962.4 1928.99  4969.5  1930.9  4991.8 1930.88
  5002.3 1932.25  5106.7 1934.05  5803.1 1936.95  5844.4  1936.5  5884.5  1938.2
  5894.5 1937.25  5914.6 1938.76  6050.7  1941.7  6105.1 1944.35  6196.3 1945.02
#Mann= 9 ,-1 , 0
  3660.9     .07       0  3841.2     .16       0  4647.2     .07       0
  4664.5     .16       0  4744.2     .07       0  5002.3     .16       0
  5106.7     .07       0  5803.1    .035       0  6050.7     .05       0
Bank Sta=4647.2,4664.5
XS Rating Curve= 0 ,0
Exp/Cntr=0.3,0.1

Type RM Length L Ch R = 1 ,14000   ,1000,1000,1000
BEGIN DESCRIPTION:
Stink Creek 27.0
END DESCRIPTION:
XS GIS Cut Line= 5
        1438205.        6871538.      1438686.96      6871780.86
      1438925.03        6872088.      1439094.49      6872201.59
      1440350.27      6872159.27
#Sta/Elev= 30
  4071.7 1948.87  4102.4 1942.76  4124.7 1940.35  4201.1 1937.51  4316.8  1935.5
  4371.2 1934.91    4398 1935.03  4452.4 1931.59  4503.9 1933.24  4750.1 1930.26
  4772.3 1929.43  4779.1 1927.54  4814.4 1930.48  4928.4 1931.84  4963.8 1930.75
  4971.9 1929.44  4977.8 1925.48  4978.3 1924.98  4995.1 1925.48  4996.8 1928.23
  5028.5  1930.4  5094.5 1930.23  5100.5 1932.21  5115.5 1930.33  5121.5 1932.39
    5197 1932.75  6064.2 1933.79  6290.1 1936.25  6389.2 1938.02  6460.5 1940.83
#Mann= 10 ,-1 , 0
  4071.7     .07       0  4201.1     .16       0  4316.8     .07       0
  4371.2     .16       0  4977.8     .07       0  4995.1     .16       0
    5197     .07       0  6064.2    .035       0  6290.1     .07       0
  6389.2    .035       0
Bank Sta=4977.8,4995.1
XS Rating Curve= 0 ,0
Exp/Cntr=0.3,0.1

Type RM Length L Ch R = 1 ,13000   ,404,404,404
BEGIN DESCRIPTION:
Stink Creek 25.0
END DESCRIPTION:
XS GIS Cut Line= 4
      1437954.99      6871787.97      1438020.65      6871971.58
      1438410.96      6872242.43      1440400.86      6872443.46
#Sta/Elev= 30
    4805 1951.44  4879.9 1950.84  4938.2 1948.96  4953.7 1943.94    4969 1934.82
    4975  1929.1    4985 1923.81  4985.5 1923.31  5003.9 1923.81  5006.9 1925.67
  5021.8 1926.11  5087.3 1926.25    5138 1927.49  5190.2 1926.62  5382.5 1925.56
  5467.8 1926.59  5539.4 1928.92  5677.4 1930.62  6494.3 1931.82  6504.3 1932.53
  6877.4 1931.81  6966.7 1932.95  7005.8 1932.29  7107.4 1932.37  7161.6 1933.35
    7228 1933.01  7367.4 1936.13  7378.8 1935.57    7429 1936.25  7475.1 1938.85
#Mann= 7 ,-1 , 0
    4805     .07       0  4879.9     .16       0    4985     .07       0
  5003.9     .16       0  5190.2     .07       0  7005.8    .035       0
  7161.6     .07       0
Bank Sta=4985,5003.9
XS Rating Curve= 0 ,0
Exp/Cntr=0.3,0.1