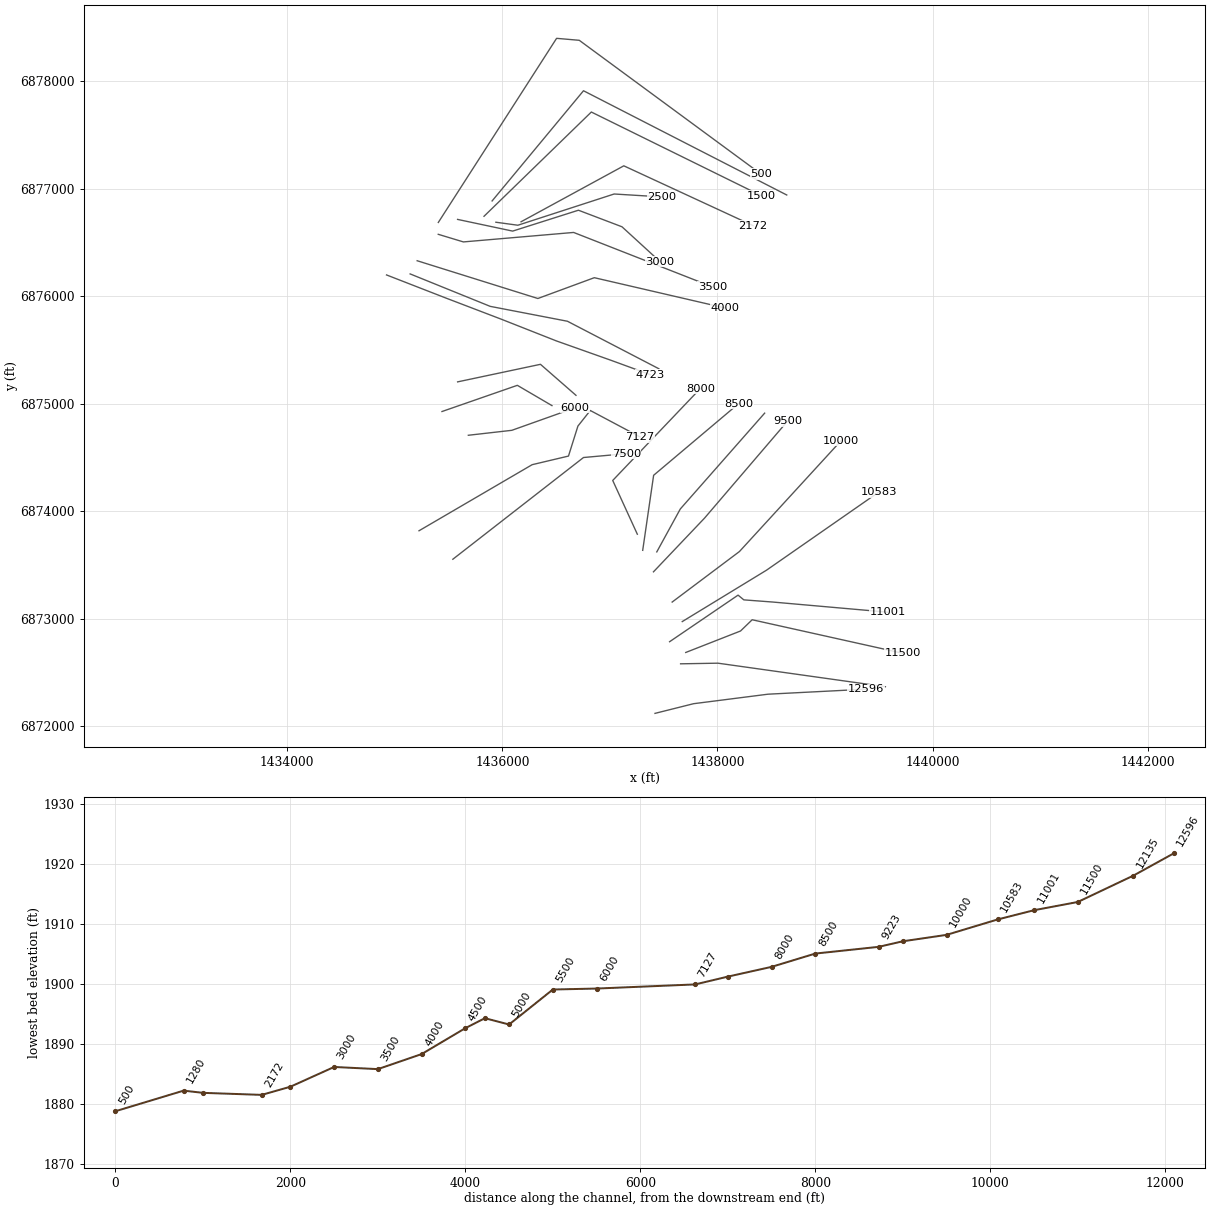
HEC-RAS study Stink Creek.prj: Stink Creek Base Level Engineering

--- Stink Creek.g01 (geometry) --- (continued)

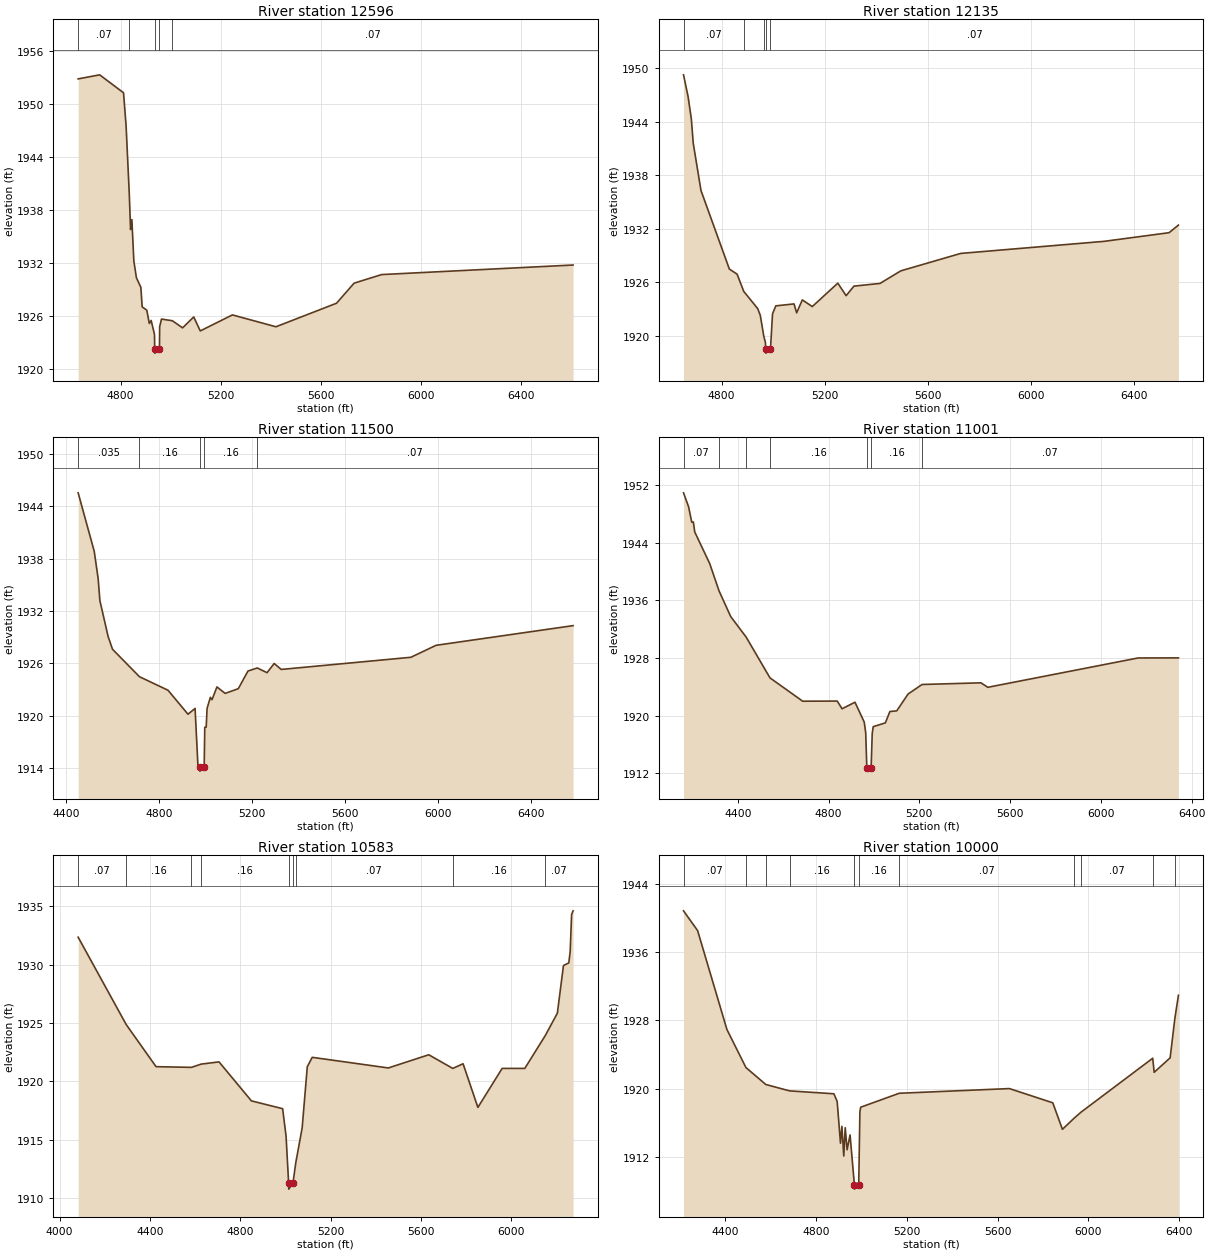
Type RM Length L Ch R = 1 ,12596   ,461,461,461
BEGIN DESCRIPTION:
Stink Creek 24.0
END DESCRIPTION:
XS GIS Cut Line= 4
      1437419.17      6872121.47      1437777.75      6872211.44
      1438469.87      6872299.91      1439378.73      6872346.36
#Sta/Elev= 30
  4630.3  1952.8  4716.2 1953.26  4811.6 1951.23  4821.9 1947.46  4834.5 1939.84
  4839.7 1935.77  4844.9  1936.9  4852.8 1932.21  4863.1 1930.32  4880.9 1929.23
    4886 1927.03  4904.4 1926.66  4914.7 1925.15    4922 1925.49  4935.3 1923.91
  4936.2  1922.3  4936.7  1921.8  4955.1  1922.3  4955.9 1924.77  4963.2 1925.65
  5006.7 1925.46  5047.6 1924.66  5092.1 1925.89  5118.2 1924.31  5246.6 1926.12
  5420.6 1924.78  5662.6 1927.44  5732.9 1929.71  5843.1 1930.68  6607.8 1931.76
#Mann= 5 ,-1 , 0
  4630.3     .07       0  4834.5     .16       0  4936.2     .07       0
  4955.1     .16       0  5006.7     .07       0
Bank Sta=4936.2,4955.1
XS Rating Curve= 0 ,0
Exp/Cntr=0.3,0.1

Type RM Length L Ch R = 1 ,12135   ,635,635,635
BEGIN DESCRIPTION:
Stink Creek 23.0
END DESCRIPTION:
XS GIS Cut Line= 3
       1437657.2      6872582.53      1438004.66      6872588.35
      1439560.94      6872369.47
#Sta/Elev= 30
  4652.5 1949.24  4670.3  1946.8  4682.8 1944.31  4690.3 1941.57  4720.3 1936.29
  4830.3  1927.5  4860.3 1926.93  4886.1    1925  4940.3 1923.07  4950.3 1922.31
  4963.6 1920.02  4970.3 1919.25  4970.9 1918.59  4971.4 1918.09  4989.8 1918.59
  4997.7 1922.49  5010.4 1923.38  5081.1  1923.6  5091.2  1922.6  5113.3 1924.05
  5151.8  1923.3  5250.8 1925.92  5283.1 1924.52  5313.4 1925.59  5414.4 1925.89
  5495.2  1927.3  5727.4 1929.25  6282.8  1930.6  6535.3 1931.57  6571.6 1932.42
#Mann= 5 ,-1 , 0
  4652.5     .07       0  4886.1     .16       0  4963.6     .07       0
  4970.9     .07       0  4989.8     .07       0
Bank Sta=4970.9,4989.8
XS Rating Curve= 0 ,0
Exp/Cntr=0.3,0.1

Type RM Length L Ch R = 1 ,11500   ,499,499,499
BEGIN DESCRIPTION:
Stink Creek 22.0
END DESCRIPTION:
XS GIS Cut Line= 4
      1437705.03      6872688.01      1438214.46       6872887.8
      1438322.57      6872992.34      1439720.45      6872681.14
#Sta/Elev= 30
  4452.8 1945.52  4521.9 1938.84  4538.7 1935.74  4546.3 1933.19  4581.7 1929.09
  4600.6 1927.63  4716.5 1924.49  4839.5 1922.94  4925.4  1920.2  4955.9 1920.86
  4968.4 1914.23  4976.2 1914.19  4976.7 1913.69  4995.1 1914.19  4997.6 1918.71
  5003.7 1918.71  5007.6 1920.87  5021.7 1922.13  5028.7 1921.86    5050 1923.32
  5085.3 1922.58  5141.9 1923.12  5183.6 1925.14  5223.6 1925.49  5265.6 1924.95
  5296.3    1926  5326.7 1925.32  5884.5 1926.71    5993 1928.08  6582.5 1930.33
#Mann= 5 ,-1 , 0
  4452.8    .035       0  4716.5     .16       0  4976.2     .07       0
  4995.1     .16       0  5223.6     .07       0
Bank Sta=4976.2,4995.1
XS Rating Curve= 0 ,0
Exp/Cntr=0.3,0.1

Type RM Length L Ch R = 1 ,11001   ,418,418,418
BEGIN DESCRIPTION:
Stink Creek 21.0
END DESCRIPTION:
XS GIS Cut Line= 5
      1437554.97      6872787.98      1438191.48      6873221.37
      1438245.03       6873177.3      1438511.74      6873157.26
      1439581.91      6873062.79
#Sta/Elev= 30
  4160.6 1950.93    4183    1949  4196.9 1946.86    4204 1946.88  4210.1  1945.5
  4275.8 1941.14  4317.3 1937.32  4368.7 1933.76  4436.8 1930.91  4541.6 1925.26
  4685.8 1922.02  4838.1 1922.04  4859.4 1920.97  4916.3 1921.88  4957.1 1919.12
  4963.6 1917.66  4968.5 1912.82    4969 1912.32  4987.4 1912.82  4992.3 1917.54
  4996.7 1918.49  5050.1 1919.01  5070.2 1920.59  5100.3 1920.68  5150.4 1923.02
    5212 1924.34  5471.5 1924.57  5501.6 1923.95  6164.2 1928.02  6341.8 1928.03
#Mann= 7 ,-1 , 0
  4160.6     .07       0  4317.3    .035       0  4436.8     .07       0
  4541.6     .16       0  4968.5     .07       0  4987.4     .16       0
    5212     .07       0
Bank Sta=4968.5,4987.4
XS Rating Curve= 0 ,0
Exp/Cntr=0.3,0.1

Type RM Length L Ch R = 1 ,10583   ,583,583,583
BEGIN DESCRIPTION:
Stink Creek 20.0
END DESCRIPTION:
XS GIS Cut Line= 3
      1437672.62      6872975.33      1438455.87      6873453.36
      1439500.38      6874180.53
#Sta/Elev= 30
  4082.4 1932.35    4295 1924.87  4427.1 1921.26  4583.9  1921.2    4627 1921.48
  4705.8 1921.67  4849.1 1918.33  4987.3 1917.66  5002.5 1915.31  5013.9 1911.27
  5014.4 1910.77  5032.8 1911.27  5045.5 1913.03  5073.8 1916.03  5096.4 1921.25
  5118.3 1922.06  5455.1 1921.15    5634 1922.28  5740.3 1921.11  5785.9 1921.51
  5851.4 1917.77  5958.7 1921.11    6059 1921.11  6149.5 1923.92  6203.1 1925.84
  6230.1 1929.92  6253.7 1930.15  6259.8 1931.11  6266.1 1934.28  6272.7 1934.61
#Mann= 9 ,-1 , 0
  4082.4     .07       0    4295     .16       0  4583.9    .035       0
    4627     .16       0  5013.9     .07       0  5032.8     .16       0
  5045.5     .07       0  5740.3     .16       0  6149.5     .07       0
Bank Sta=5013.9,5032.8
XS Rating Curve= 0 ,0
Exp/Cntr=0.3,0.1

Type RM Length L Ch R = 1 ,10000   ,500,500,500
BEGIN DESCRIPTION:
Stink Creek 19.0
END DESCRIPTION:
XS GIS Cut Line= 3
      1437578.77      6873156.94      1438204.28      6873626.92
      1439147.63      6874656.64
#Sta/Elev= 30
  4217.6 1940.86  4279.7 1938.54  4408.8 1926.93  4492.4 1922.47  4579.8 1920.48
  4684.8 1919.73  4879.5 1919.39  4894.1  1918.5  4908.7 1913.59  4914.9 1915.57
  4923.2 1912.09  4929.5 1915.41  4937.8 1912.82  4950.9 1914.56  4969.9  1908.7
  4970.4  1908.2    4989  1908.7  4994.1 1917.23  4997.3 1917.81  5167.3 1919.45
  5652.4    1920  5843.3 1918.33  5885.8 1915.22  5937.9 1916.54    5968 1917.24
  6283.3 1923.56  6289.7 1921.91    6360 1923.61  6380.9 1928.26  6396.5 1930.95
#Mann= 11 ,-1 , 0
  4217.6     .07       0  4492.4     .16       0  4579.8    .035       0
  4684.8     .16       0  4969.9     .07       0    4989     .16       0
  5167.3     .07       0  5937.9     .16       0    5968     .07       0
  6283.3    .035       0  6380.9     .07       0
Bank Sta=4969.9,4989
XS Rating Curve= 0 ,0
Exp/Cntr=0.3,0.1

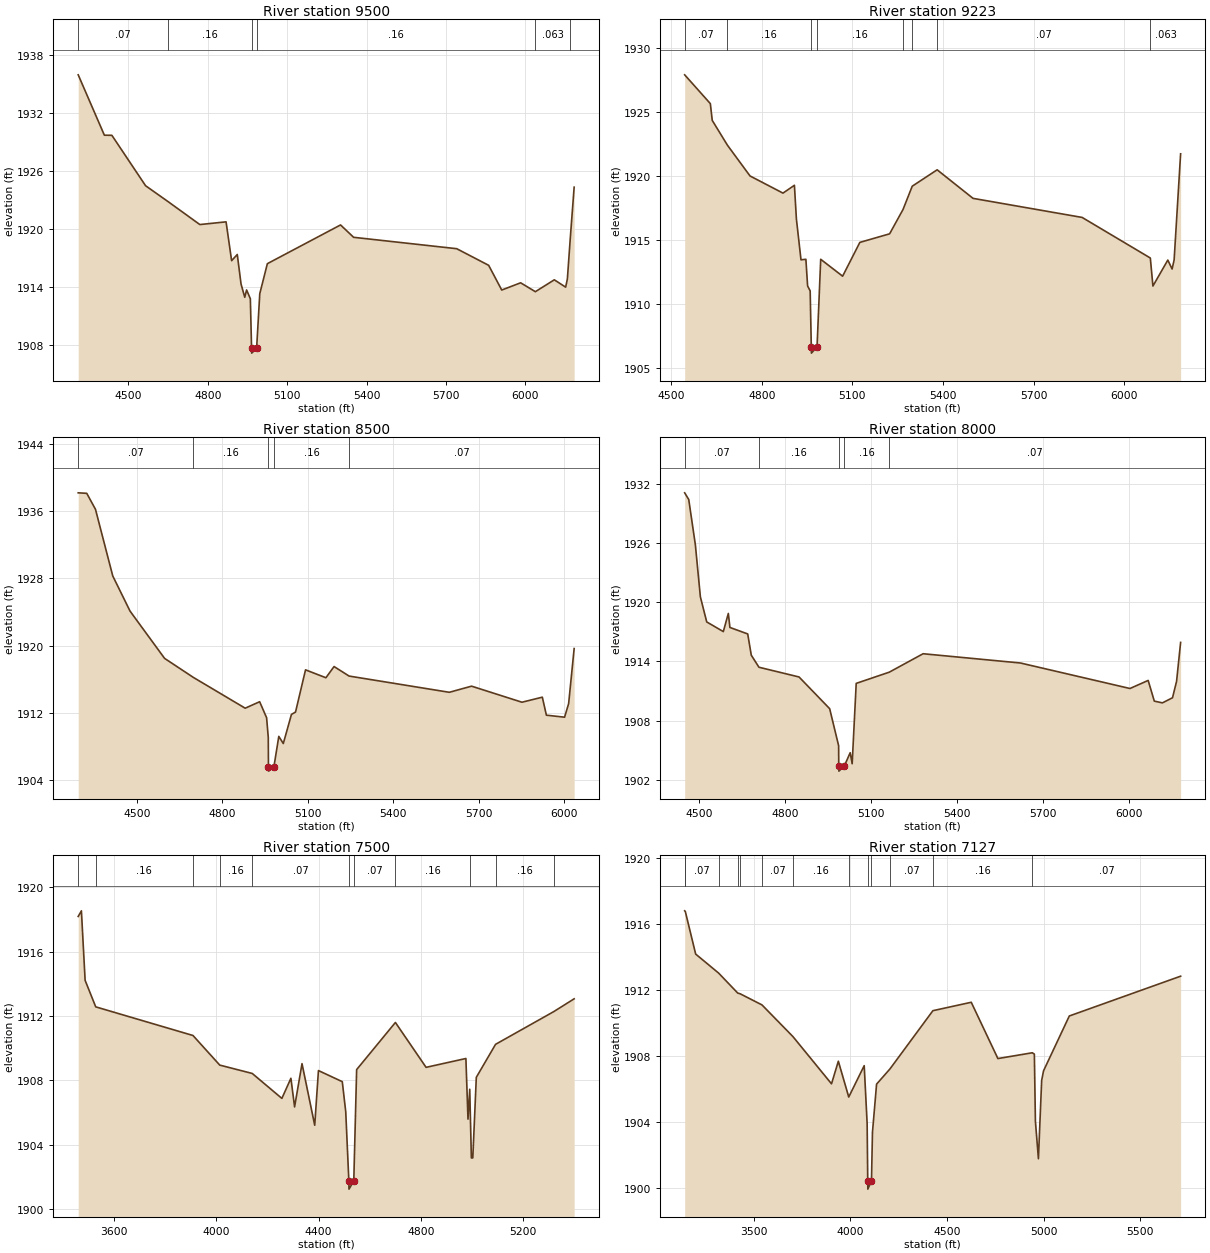
Type RM Length L Ch R = 1 ,9500    ,277,277,277
BEGIN DESCRIPTION:
Stink Creek 18.0
END DESCRIPTION:
XS GIS Cut Line= 3
      1437405.03      6873438.03      1437880.19       6873938.2
      1438650.09      6874838.37
#Sta/Elev= 30
  4310.1 1935.94    4409 1929.69  4437.3 1929.68  4564.7 1924.46  4650.5  1922.8
  4769.8 1920.44  4868.9 1920.72  4889.9  1916.7  4911.3 1917.34  4925.5 1914.29
  4939.6 1912.91  4946.5 1913.67  4960.7 1912.76  4965.3 1907.63  4965.8 1907.13
  4984.4 1907.63  4996.3 1913.28    5025 1916.39  5301.6  1920.4    5351 1919.12
  5740.7 1917.94  5861.4 1916.22  5910.8 1913.66  5982.2 1914.41    6038 1913.49
  6109.5 1914.72  6152.4 1913.96  6158.9 1914.81  6169.9 1919.03  6184.5 1924.31
#Mann= 6 ,-1 , 0
  4310.1     .07       0  4650.5     .16       0  4965.3     .07       0
  4984.4     .16       0    6038    .063       0  6169.9     .07       0
Bank Sta=4965.3,4984.4
XS Rating Curve= 0 ,0
Exp/Cntr=0.3,0.1

Type RM Length L Ch R = 1 ,9223    ,723,723,723
BEGIN DESCRIPTION:
Stink Creek 17.0
END DESCRIPTION:
XS GIS Cut Line= 3
       1437435.9      6873623.45      1437654.48      6874022.74
      1438438.56      6874914.17
#Sta/Elev= 30
  4544.8 1927.94  4629.8 1925.69  4636.1 1924.38  4686.2 1922.45  4761.2 1920.04
  4870.3  1918.7  4908.2 1919.31  4914.8 1916.68    4930 1913.49  4946.2 1913.53
  4951.9 1911.45  4960.4 1911.06  4964.1  1906.7  4964.6  1906.2  4983.2  1906.7
  4995.3 1913.53  5067.9 1912.21  5124.9 1914.85  5223.5 1915.52  5267.9 1917.42
  5298.4 1919.24  5380.9 1920.52  5499.8 1918.29  5861.1  1916.8  6086.9 1913.63
  6095.5 1911.44  6144.8 1913.47    6159 1912.77  6165.7 1913.48  6187.2 1921.77
#Mann= 8 ,-1 , 0
  4544.8     .07       0  4686.2     .16       0  4964.1     .07       0
  4983.2     .16       0  5267.9     .07       0  5298.4     .16       0
  5380.9     .07       0  6086.9    .063       0
Bank Sta=4964.1,4983.2
XS Rating Curve= 0 ,0
Exp/Cntr=0.3,0.1

Type RM Length L Ch R = 1 ,8500    ,500,500,500
BEGIN DESCRIPTION:
Stink Creek 16.0
END DESCRIPTION:
XS GIS Cut Line= 3
        1437305.      6873638.03      1437406.51      6874336.09
      1438197.32      6875003.33
#Sta/Elev= 30
  4294.6 1938.16  4324.6  1938.1  4355.2  1936.2  4415.8 1928.28  4476.5  1924.1
  4597.7 1918.48  4698.6 1916.22  4880.5 1912.56  4931.2 1913.33  4955.6 1911.43
  4961.5 1909.08  4962.1 1905.58  4962.6 1905.08  4981.2 1905.58  4998.4 1909.21
  5014.2 1908.36  5042.8 1911.82  5057.1  1912.1  5092.2 1917.12  5163.7 1916.18
  5192.3 1917.51    5245 1916.38  5596.7 1914.45  5674.7 1915.18  5851.6 1913.27
    5923 1913.87  5937.3 1911.73  6001.1 1911.49  6015.4 1913.11  6034.7 1919.65
#Mann= 5 ,-1 , 0
  4294.6     .07       0  4698.6     .16       0  4962.1     .07       0
  4981.2     .16       0    5245     .07       0
Bank Sta=4962.1,4981.2
XS Rating Curve= 0 ,0
Exp/Cntr=0.3,0.1

Type RM Length L Ch R = 1 ,8000    ,500,500,500
BEGIN DESCRIPTION:
Stink Creek 15.0
END DESCRIPTION:
XS GIS Cut Line= 3
      1437254.99      6873788.03      1437026.27      6874287.99
      1437840.22      6875142.74
#Sta/Elev= 30
  4450.2 1931.12  4464.4 1930.44  4487.4 1925.86    4505 1920.55  4527.1 1918.01
    4585 1917.03  4602.5 1918.87    4608 1917.45  4670.1 1916.79  4682.6 1914.63
  4709.3 1913.41  4849.2 1912.42    4956  1909.2  4987.3 1905.44  4987.7 1903.36
  4988.2 1902.86  5006.8 1903.36  5027.6 1904.73  5034.5 1903.61  5048.6 1911.77
  5164.1 1912.91    5282 1914.78  5621.4 1913.84  6003.6 1911.25  6067.1 1912.07
  6088.5 1909.97  6116.8 1909.79    6152 1910.31  6166.2 1911.98  6180.3 1915.93
#Mann= 5 ,-1 , 0
  4450.2     .07       0  4709.3     .16       0  4987.7     .07       0
  5006.8     .16       0  5164.1     .07       0
Bank Sta=4987.7,5006.8
XS Rating Curve= 0 ,0
Exp/Cntr=0.3,0.1

Type RM Length L Ch R = 1 ,7500    ,373,373,373
BEGIN DESCRIPTION:
Stink Creek 14.0
END DESCRIPTION:
XS GIS Cut Line= 3
      1435540.12      6873555.35       1436754.6      6874501.44
      1437151.79      6874537.27
#Sta/Elev= 30
  3460.5 1918.18    3473 1918.53  3487.5 1914.21    3529 1912.56  3909.1 1910.78
  4013.7 1908.94  4140.7 1908.42  4256.5 1906.87  4291.8 1908.12  4306.2 1906.34
  4335.2 1909.03  4384.9  1905.2  4399.4  1908.6  4492.6 1907.91  4506.1 1906.04
  4518.3 1901.73  4518.8 1901.23  4537.5 1901.73  4548.7 1908.66  4700.2 1911.59
  4820.1  1908.8  4975.7 1909.35  4983.9 1905.58  4990.7 1907.44  4997.1 1903.17
  5002.7 1903.17  5016.4 1908.18  5091.6 1910.23  5318.6 1912.26  5398.8 1913.06
#Mann= 11 ,-1 , 0
  3460.5     .07       0    3529     .16       0  3909.1     .07       0
  4013.7     .16       0  4140.7     .07       0  4518.3     .07       0
  4537.5     .07       0  4700.2     .16       0  4990.7     .07       0
  5091.6     .16       0  5318.6     .07       0
Bank Sta=4518.3,4537.5
XS Rating Curve= 0 ,0
Exp/Cntr=0.3,0.1

Type RM Length L Ch R = 1 ,7127    ,1127,1127,1127
BEGIN DESCRIPTION:
Stink Creek 13.0
END DESCRIPTION:
XS GIS Cut Line= 6
      1435225.65      6873820.13      1436277.25      6874434.76
      1436614.99      6874514.91      1436702.74       6874793.9
      1436817.67       6874938.9      1437280.11      6874692.95
#Sta/Elev= 30
  3142.2 1916.79  3145.5 1916.75  3199.1 1914.17  3317.7 1913.02  3416.6 1911.81
    3430 1911.76  3542.3 1911.09  3702.5 1909.17  3902.1 1906.31  3937.5 1907.68
  3991.3 1905.51  4071.3 1907.41  4086.5 1903.91  4089.6 1900.43  4090.1 1899.93
  4108.9 1900.43  4114.1 1903.38  4135.3 1906.29  4204.5 1907.21  4426.8 1910.74
  4625.3 1911.25  4763.2 1907.84    4941 1908.19  4951.9 1908.11  4957.3 1904.04
  4972.9 1901.77  4989.7 1906.52  4999.5  1907.1  5132.8 1910.42  5708.8 1912.83
#Mann= 13 ,-1 , 0
  3142.2    .035       0  3145.5     .07       0  3317.7    .035       0
  3416.6     .07       0    3430    .035       0  3542.3     .07       0
  3702.5     .16       0  3991.3    .033       0  4089.6     .07       0
  4108.9    .033       0  4204.5     .07       0  4426.8     .16       0
    4941     .07       0
Bank Sta=4089.6,4108.9
XS Rating Curve= 0 ,0
Exp/Cntr=0.3,0.1

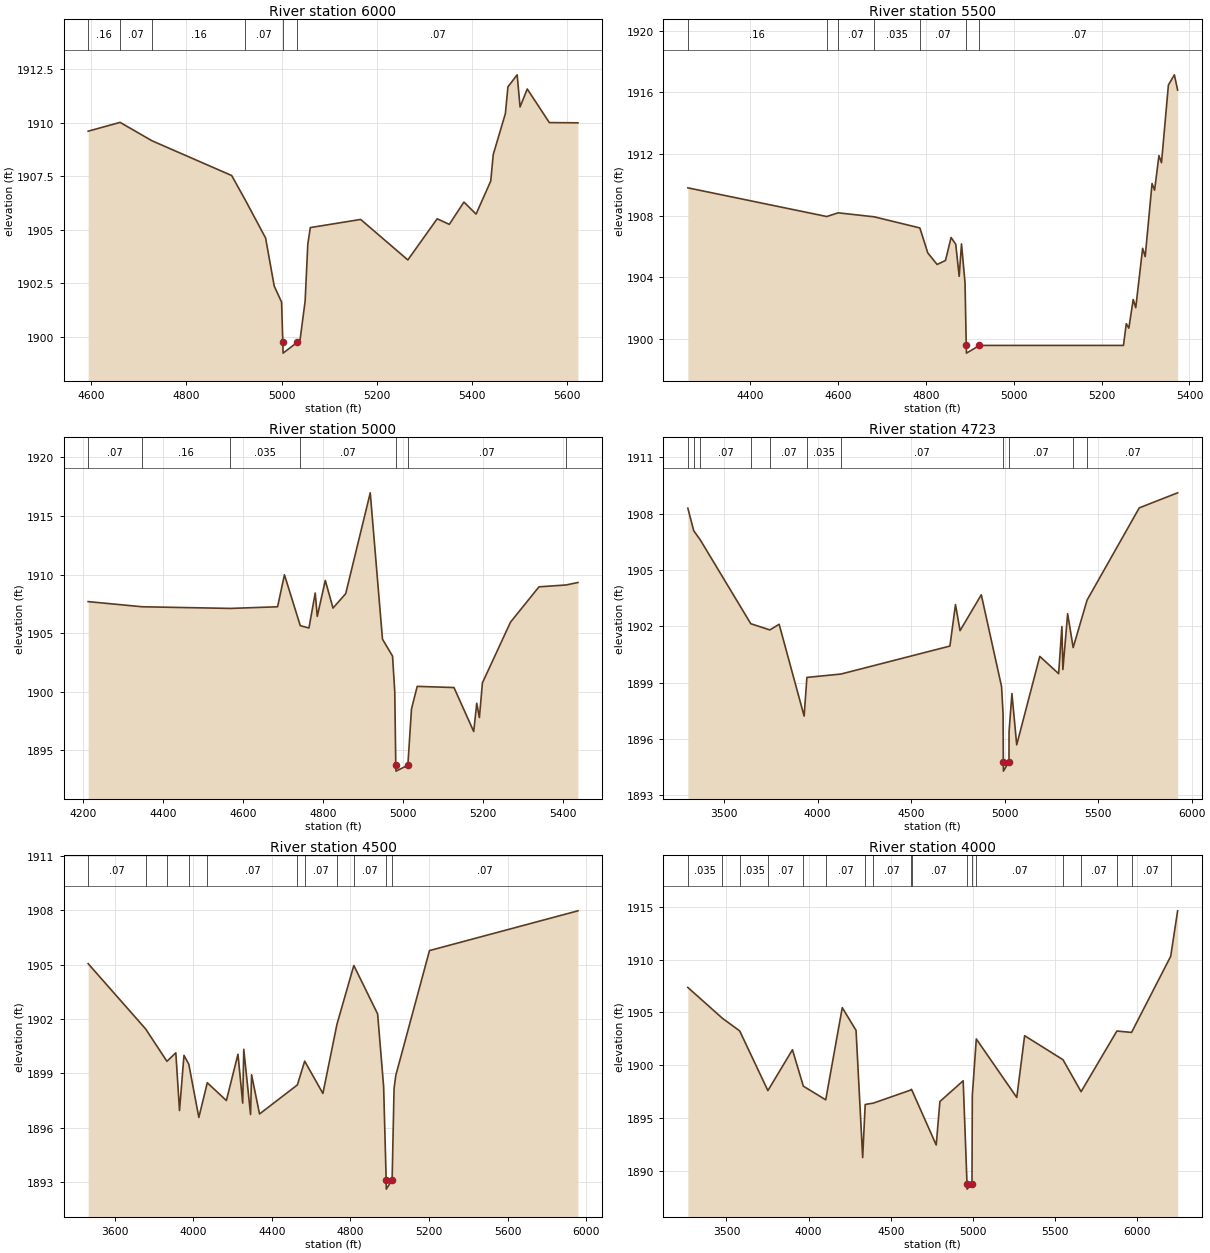
Type RM Length L Ch R = 1 ,6000    ,500,500,500
BEGIN DESCRIPTION:
Stink Creek 11.0
END DESCRIPTION:
XS GIS Cut Line= 3
      1435684.15      6874708.45      1436088.35      6874754.42
      1436675.39      6874963.61
#Sta/Elev= 30
  4593.2  1909.6  4660.4 1910.01  4727.6 1909.15    4895 1907.53  4923.6 1906.39
  4966.4 1904.61  4984.5 1902.37    5000 1901.62  5002.6 1899.74  5003.1 1899.24
  5032.7 1899.74  5038.9 1899.87  5049.5 1901.67  5055.1 1904.32  5060.4  1905.1
  5166.3 1905.48  5265.5 1903.59  5327.2 1905.51  5352.7 1905.25  5383.5 1906.29
    5409 1905.73  5439.8 1907.27  5445.1 1908.51  5470.6 1910.42    5476 1911.67
  5495.4 1912.23  5501.5 1910.73  5516.6 1911.57  5563.1    1910  5623.2 1909.99
#Mann= 6 ,-1 , 0
  4593.2     .16       0  4660.4     .07       0  4727.6     .16       0
  4923.6     .07       0  5002.6     .07       0  5032.7     .07       0
Bank Sta=5002.6,5032.7
XS Rating Curve= 0 ,0
Exp/Cntr=0.3,0.1

Type RM Length L Ch R = 1 ,5500    ,500,500,500
BEGIN DESCRIPTION:
Stink Creek 10.0
END DESCRIPTION:
XS GIS Cut Line= 3
      1435439.25      6874929.35       1436139.6      6875172.93
       1436461.4      6874984.32
#Sta/Elev= 30
  4258.5  1909.8  4574.6 1907.94  4600.6 1908.18  4682.6 1907.92  4786.4  1907.2
  4804.5 1905.58  4825.7 1904.83  4844.8 1905.09  4857.5 1906.58  4868.1 1906.14
  4875.9 1904.06  4881.2 1906.16  4889.2 1903.65    4892 1899.58  4892.5 1899.08
  4922.1 1899.58  5249.7 1899.58  5256.2 1900.99    5262  1900.7  5271.9 1902.56
  5277.7 1902.03  5293.4 1905.88  5299.2 1905.34  5314.8 1910.08  5320.6 1909.65
  5330.5 1911.89  5336.3 1911.43    5352 1916.47  5365.6 1917.13    5373 1916.14
#Mann= 7 ,-1 , 0
  4258.5     .16       0  4574.6    .035       0  4600.6     .07       0
  4682.6    .035       0  4786.4     .07       0    4892     .07       0
  4922.1     .07       0
Bank Sta=4892,4922.1
XS Rating Curve= 0 ,0
Exp/Cntr=0.3,0.1

Type RM Length L Ch R = 1 ,5000    ,277,277,277
BEGIN DESCRIPTION:
Stink Creek 9.0
END DESCRIPTION:
XS GIS Cut Line= 3
      1435584.48       6875205.1      1436354.57      6875368.36
      1436684.71      6875079.92
#Sta/Elev= 30
  4212.8  1907.7    4348 1907.26  4568.9 1907.12  4686.8 1907.26    4704 1909.99
  4743.6 1905.65  4765.3 1905.45    4781 1908.43  4786.1 1906.44  4806.2 1909.51
  4825.5 1907.15  4857.3 1908.38  4918.7 1916.98  4949.3  1904.5  4974.5 1903.05
    4980 1900.03  4982.6 1893.74  4983.1 1893.24  5012.8 1893.74  5021.9 1898.54
  5036.2 1900.47  5128.2 1900.37  5177.6 1896.62  5185.2 1899.03  5191.8 1897.81
  5199.4 1900.77  5269.7 1905.95  5340.9 1908.96  5408.6 1909.12  5438.4 1909.33
#Mann= 7 ,-1 , 0
  4212.8     .07       0    4348     .16       0  4568.9    .035       0
  4743.6     .07       0  4982.6     .07       0  5012.8     .07       0
  5408.6    .035       0
Bank Sta=4982.6,5012.8
XS Rating Curve= 0 ,0
Exp/Cntr=0.3,0.1

Type RM Length L Ch R = 1 ,4723    ,223,223,223
BEGIN DESCRIPTION:
Stink Creek 8.1
END DESCRIPTION:
XS GIS Cut Line= 6
      1434923.62      6876199.72      1435469.61      6875987.04
      1435988.55      6875788.69      1436502.89      6875585.83
      1437014.32      6875404.32      1437373.38      6875272.73
#Sta/Elev= 30
  3305.6 1908.29  3337.2 1907.09  3371.7 1906.61  3642.2 1902.14    3744 1901.81
  3793.9 1902.11  3927.5 1897.22  3942.4 1899.28  4124.5 1899.46  4707.3 1900.95
    4737 1903.16  4761.4 1901.77    4875 1903.68  4983.3  1898.8  4991.5 1897.34
  4992.9 1894.79  4993.4 1894.29  5023.1 1894.79  5023.5 1896.39  5038.9 1898.42
  5064.4 1895.69  5187.9  1900.4  5288.7 1899.48  5306.1 1901.99  5311.4  1899.7
  5336.9 1902.67  5366.4 1900.87  5440.9  1903.4    5720 1908.31  5925.1 1909.11
#Mann= 11 ,-1 , 0
  3305.6     .07       0  3337.2    .035       0  3371.7     .07       0
  3642.2    .035       0    3744     .07       0  3942.4    .035       0
  4124.5     .07       0  4992.9     .07       0  5023.1     .07       0
  5366.4    .035       0  5440.9     .07       0
Bank Sta=4992.9,5023.1
XS Rating Curve= 0 ,0
Exp/Cntr=0.3,0.1

Type RM Length L Ch R = 1 ,4500    ,500,500,500
BEGIN DESCRIPTION:
Stink Creek 8.0
END DESCRIPTION:
XS GIS Cut Line= 4
      1435143.09      6876209.19      1435887.46      6875907.42
      1436605.22      6875769.01      1437455.11      6875327.14
#Sta/Elev= 30
  3465.8 1905.05  3758.6 1901.45  3866.6 1899.67  3911.9 1900.14  3930.6 1896.96
  3953.4    1900  3977.9 1899.51    4029 1896.58  4072.1 1898.49  4169.1 1897.51
  4228.1 1900.06  4252.2 1897.37  4257.6 1900.33  4292.2 1896.74  4297.3 1898.93
  4337.8 1896.77  4530.4 1898.37  4567.5 1899.68  4660.3  1897.9  4731.7 1901.71
  4817.6 1904.95  4938.7 1902.28  4969.2 1898.28  4982.2 1893.13  4982.7 1892.63
  5012.4 1893.13  5022.3 1898.17  5031.3  1898.9  5202.6 1905.77  5957.9 1907.96
#Mann= 11 ,-1 , 0
  3465.8     .07       0  3758.6    .035       0  3866.6     .07       0
  3977.9    .035       0  4072.1     .07       0  4530.4    .035       0
  4567.5     .07       0  4731.7    .035       0  4817.6     .07       0
  4982.2     .07       0  5012.4     .07       0
Bank Sta=4982.2,5012.4
XS Rating Curve= 0 ,0
Exp/Cntr=0.3,0.1

Type RM Length L Ch R = 1 ,4000    ,500,500,500
BEGIN DESCRIPTION:
Stink Creek 7.0
END DESCRIPTION:
XS GIS Cut Line= 4
      1435208.41      6876331.81      1436330.35      6875980.59
      1436855.06      6876174.13       1438067.7      6875893.01
#Sta/Elev= 30
  3265.1 1907.36  3475.9 1904.44  3580.6 1903.25    3752 1897.61  3901.5 1901.47
  3967.7 1898.03  4103.9 1896.74  4204.6 1905.45  4288.4  1903.3  4328.7 1891.28
    4344  1896.3  4394.1 1896.43  4620.5 1897.66  4625.9 1897.73  4776.1 1892.47
  4798.6 1896.58  4940.1 1898.54  4963.5  1888.8    4964  1888.3  4993.7  1888.8
  4995.7 1897.14    5020 1902.49  5266.2 1896.96    5314  1902.8  5547.3 1900.53
  5657.5 1897.51  5875.2 1903.24  5964.5 1903.11  6202.6  1910.3  6244.8  1914.6
#Mann= 18 ,-1 , 0
  3265.1    .035       0  3475.9     .07       0  3580.6    .035       0
    3752     .07       0  3967.7    .035       0  4103.9     .07       0
    4344    .035       0  4394.1     .07       0  4620.5    .035       0
  4625.9     .07       0  4963.5     .07       0  4993.7     .07       0
    5020     .07       0  5547.3    .035       0  5657.5     .07       0
  5875.2    .035       0  5964.5     .07       0  6202.6    .035       0
Bank Sta=4963.5,4993.7
XS Rating Curve= 0 ,0
Exp/Cntr=0.3,0.1

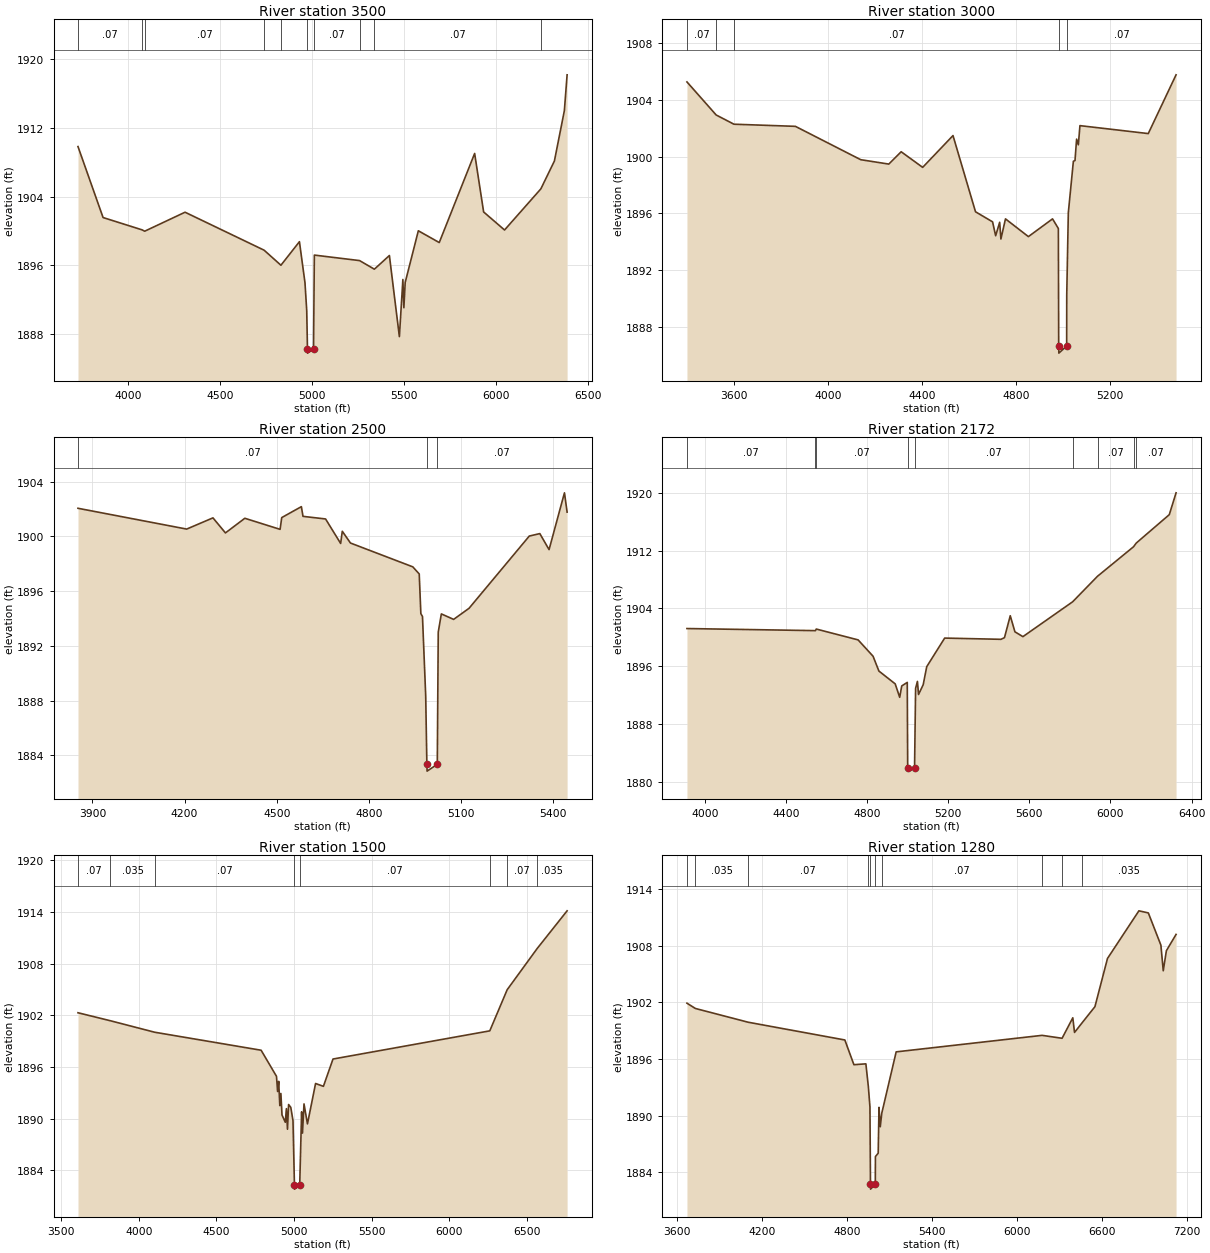
Type RM Length L Ch R = 1 ,3500    ,500,500,500
BEGIN DESCRIPTION:
Stink Creek 6.0
END DESCRIPTION:
XS GIS Cut Line= 4
      1435404.46      6876577.63      1435638.01      6876506.87
       1436662.8      6876595.02      1437954.99      6876088.01
#Sta/Elev= 30
  3727.4 1909.83  3863.8 1901.57  4075.6 1900.14  4090.3 1899.98  4309.7 1902.19
  4739.9 1897.77  4831.3 1896.02    4932 1898.76  4962.1    1894  4971.7 1890.73
  4975.7 1886.29  4976.2 1885.79  5008.7 1886.29  5013.1  1897.2  5259.2 1896.56
  5339.6 1895.56  5421.4 1897.15  5475.7 1887.71  5494.7 1894.36  5500.1 1891.07
  5507.3 1894.01  5578.8 1900.03  5692.6 1898.66  5885.1 1909.03    5934 1902.22
  6047.8 1900.12  6245.4 1904.91    6319 1908.15  6373.2 1914.01  6388.1 1918.18
#Mann= 10 ,-1 , 0
  3727.4     .07       0  4075.6    .035       0  4090.3     .07       0
  4739.9    .035       0  4831.3     .07       0  4975.7     .07       0
  5008.7     .07       0  5259.2     .16       0  5339.6     .07       0
  6245.4    .035       0
Bank Sta=4975.7,5008.7
XS Rating Curve= 0 ,0
Exp/Cntr=0.3,0.1

Type RM Length L Ch R = 1 ,3000    ,500,500,500
BEGIN DESCRIPTION:
Stink Creek 5.0
END DESCRIPTION:
XS GIS Cut Line= 5
       1435584.2      6876716.27      1436096.03      6876607.48
      1436707.54      6876801.73      1437112.51      6876647.57
       1437466.8      6876322.99
#Sta/Elev= 30
  3401.8 1905.26    3526 1902.93  3601.7 1902.28  3862.7 1902.13  4140.3 1899.78
  4259.7 1899.47  4312.2 1900.34  4403.6 1899.24  4532.5 1901.48  4628.2 1896.11
  4700.7  1895.4  4713.8 1894.42  4730.8 1895.37  4736.1 1894.19  4755.5 1895.61
  4852.9 1894.36  4955.6 1895.61  4980.3 1894.93  4981.7 1886.65  4982.4 1886.15
  5015.6 1886.65  5015.9 1890.24  5022.6 1896.04  5044.1 1899.67    5051 1899.72
  5057.8 1901.23  5065.2 1900.83    5072 1902.18  5362.4 1901.62  5480.5 1905.76
#Mann= 5 ,-1 , 0
  3401.8     .07       0    3526    .035       0  3601.7     .07       0
  4981.7     .07       0  5015.6     .07       0
Bank Sta=4981.7,5015.6
XS Rating Curve= 0 ,0
Exp/Cntr=0.3,0.1

Type RM Length L Ch R = 1 ,2500    ,328,328,328
BEGIN DESCRIPTION:
Stink Creek 4.0
END DESCRIPTION:
XS GIS Cut Line= 4
      1435940.36        6876690.      1436144.48      6876662.15
      1437039.51      6876952.62      1437483.59      6876925.55
#Sta/Elev= 30
    3853 1902.06  4206.7 1900.54  4292.3 1901.36  4332.9 1900.26    4396 1901.33
  4510.8 1900.52  4516.1 1901.38    4580 1902.18  4585.3 1901.47  4658.8 1901.28
  4707.9 1899.49  4713.2 1900.38  4739.9 1899.52  4942.7 1897.78  4963.6 1897.26
  4968.9 1894.36  4974.2 1894.15  4984.7 1888.34  4988.5 1883.35  4989.2 1882.85
  5022.4 1883.35  5025.5 1893.01  5035.6 1894.34  5075.6 1893.94  5125.7 1894.75
  5321.8 1900.03  5356.1 1900.21  5386.2 1899.04  5436.3 1903.19  5444.9 1901.78
#Mann= 3 ,-1 , 0
    3853     .07       0  4988.5     .07       0  5022.4     .07       0
Bank Sta=4988.5,5022.4
XS Rating Curve= 0 ,0
Exp/Cntr=0.3,0.1

Type RM Length L Ch R = 1 ,2172    ,672,672,672
BEGIN DESCRIPTION:
Stink Creek 3.0
END DESCRIPTION:
XS GIS Cut Line= 3
      1436174.13      6876694.24      1437129.31      6877214.75
      1438330.08      6876658.87
#Sta/Elev= 30
  3912.2 1901.21  4545.7 1900.92  4549.6 1901.14  4755.9 1899.64  4829.6 1897.38
  4858.4 1895.33  4938.7 1893.56  4960.9  1891.7    4971 1893.27  4998.2 1893.76
  5000.3 1881.99    5001 1881.49  5034.2 1881.99  5039.3 1892.94  5048.3  1893.9
  5053.8 1892.09  5076.7 1893.44  5094.2 1895.94  5182.6 1899.89    5460 1899.72
  5477.4 1899.95  5505.9 1902.98  5528.8 1900.76  5568.3 1900.09  5813.4 1904.91
    5936 1908.44  6113.5 1912.52  6127.3 1913.04  6289.8 1916.96  6323.2 1919.98
#Mann= 9 ,-1 , 0
  3912.2     .07       0  4545.7    .035       0  4549.6     .07       0
  5000.3     .07       0  5034.2     .07       0  5813.4    .035       0
    5936     .07       0  6113.5    .035       0  6127.3     .07       0
Bank Sta=5000.3,5034.2
XS Rating Curve= 0 ,0
Exp/Cntr=0.3,0.1

Type RM Length L Ch R = 1 ,1500    ,220,220,220
BEGIN DESCRIPTION:
Stink Creek 2.0
END DESCRIPTION:
XS GIS Cut Line= 3
      1435829.82      6876745.37      1436827.41      6877715.17
      1438404.97      6876938.01
#Sta/Elev= 30
  3608.7  1902.3  3817.8 1901.37  4102.4 1900.04  4788.1 1897.95  4887.1 1894.92
  4894.2 1893.16  4901.2 1894.34  4908.4 1891.52  4915.4 1892.93  4922.5 1890.44
  4943.7 1889.59  4950.8 1891.17  4957.8 1888.78    4965 1891.65  4979.1 1891.32
  4993.3 1889.78  5002.6 1882.33  5003.3 1881.83  5036.6 1882.33  5048.8  1890.8
  5054.4 1888.33  5064.2 1891.72  5086.5  1889.4  5138.7 1894.09  5189.2 1893.76
    5251 1896.93  6260.7  1900.2  6372.6 1904.97  6565.6 1909.75  6758.6 1914.13
#Mann= 8 ,-1 , 0
  3608.7     .07       0  3817.8    .035       0  4102.4     .07       0
  5002.6     .07       0  5036.6     .07       0  6260.7    .035       0
  6372.6     .07       0  6565.6    .035       0
Bank Sta=5002.6,5036.6
XS Rating Curve= 0 ,0
Exp/Cntr=0.3,0.1

Type RM Length L Ch R = 1 ,1280    ,780,780,780
BEGIN DESCRIPTION:
Stink Creek 1.0
END DESCRIPTION:
XS GIS Cut Line= 3
      1435905.02      6876888.02      1436754.59        6877913.
       1438643.9      6876943.37
#Sta/Elev= 30
  3668.7 1901.91  3728.3 1901.35  4101.6 1899.89  4784.1 1898.01    4848 1895.39
  4932.6 1895.48    4950 1893.07  4961.3 1890.92  4965.1  1882.7  4965.8  1882.2
  4999.1  1882.7    5000 1885.65  5019.6 1886.01  5025.2 1890.87  5034.2 1888.81
  5044.9 1890.25  5146.6 1896.75  6177.3  1898.5  6318.5 1898.19  6394.2 1900.36
  6406.4 1898.81  6461.5 1899.86  6550.5 1901.54  6639.2 1906.65  6861.1  1911.7
  6927.7 1911.48  7016.5 1908.06  7033.1 1905.35  7055.2 1907.47  7123.6  1909.2
#Mann= 10 ,-1 , 0
  3668.7     .07       0  3728.3    .035       0  4101.6     .07       0
    4950    .035       0  4965.1    .035       0  4999.1    .035       0
  5044.9     .07       0  6177.3    .035       0  6318.5     .07       0
  6461.5    .035       0
Bank Sta=4965.1,4999.1
XS Rating Curve= 0 ,0
Exp/Cntr=0.3,0.1

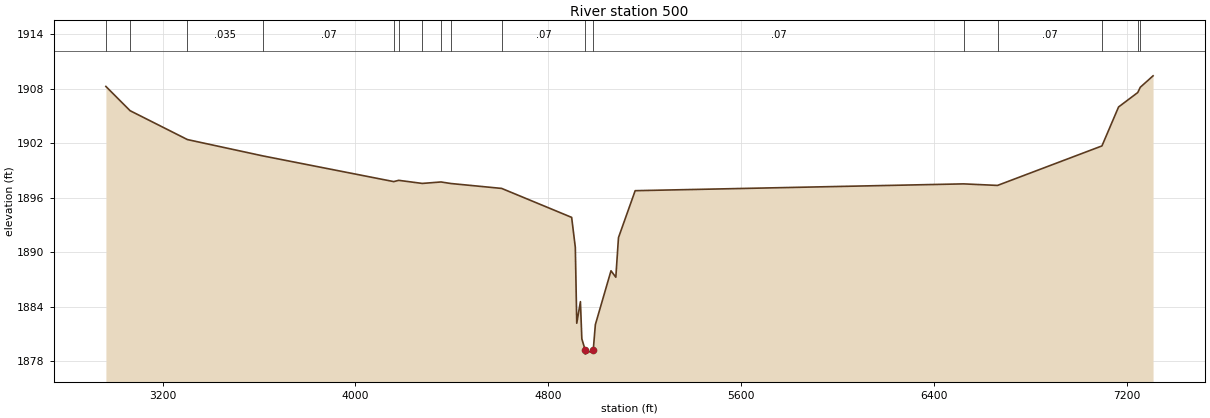
Type RM Length L Ch R = 1 ,500     ,0,0,0
BEGIN DESCRIPTION:
Stink Creek 3758
END DESCRIPTION:
XS GIS Cut Line= 4
      1435405.03      6876688.04      1436504.47       6878400.6
      1436715.33      6878382.26      1438404.98      6877138.01
#Sta/Elev= 30
  2964.9 1908.24  3065.3 1905.57  3303.1 1902.39  3616.4 1900.59  4159.3 1897.76
  4179.9  1897.9  4277.8 1897.56  4355.4 1897.72  4396.2 1897.55  4607.1 1897.01
  4897.5 1893.82  4912.7 1890.53  4918.7 1882.16  4933.9 1884.54  4939.8 1880.44
  4953.2 1879.26  4953.8 1878.76  4987.3 1879.26  4995.9 1882.01  5060.8 1887.94
  5080.8 1887.23  5091.8 1891.59  5161.1 1896.76  6523.6 1897.51  6664.7 1897.34
  7097.9 1901.69  7166.9 1905.98  7246.5 1907.57    7257 1908.15    7310 1909.41
#Mann= 17 ,-1 , 0
  2964.9    .035       0  3065.3     .07       0  3303.1    .035       0
  3616.4     .07       0  4159.3    .035       0  4179.9     .07       0
  4277.8    .035       0  4355.4     .07       0  4396.2    .035       0
  4607.1     .07       0  4953.2     .07       0  4987.3     .07       0
  6523.6    .035       0  6664.7     .07       0  7097.9    .035       0
  7246.5     .07       0    7257    .035       0
Bank Sta=4953.2,4987.3
XS Rating Curve= 0 ,0
Exp/Cntr=0.3,0.1

Chan Stop Cuts=-1
Use User Specified Reach Order=0
Composite Channel Slope=5