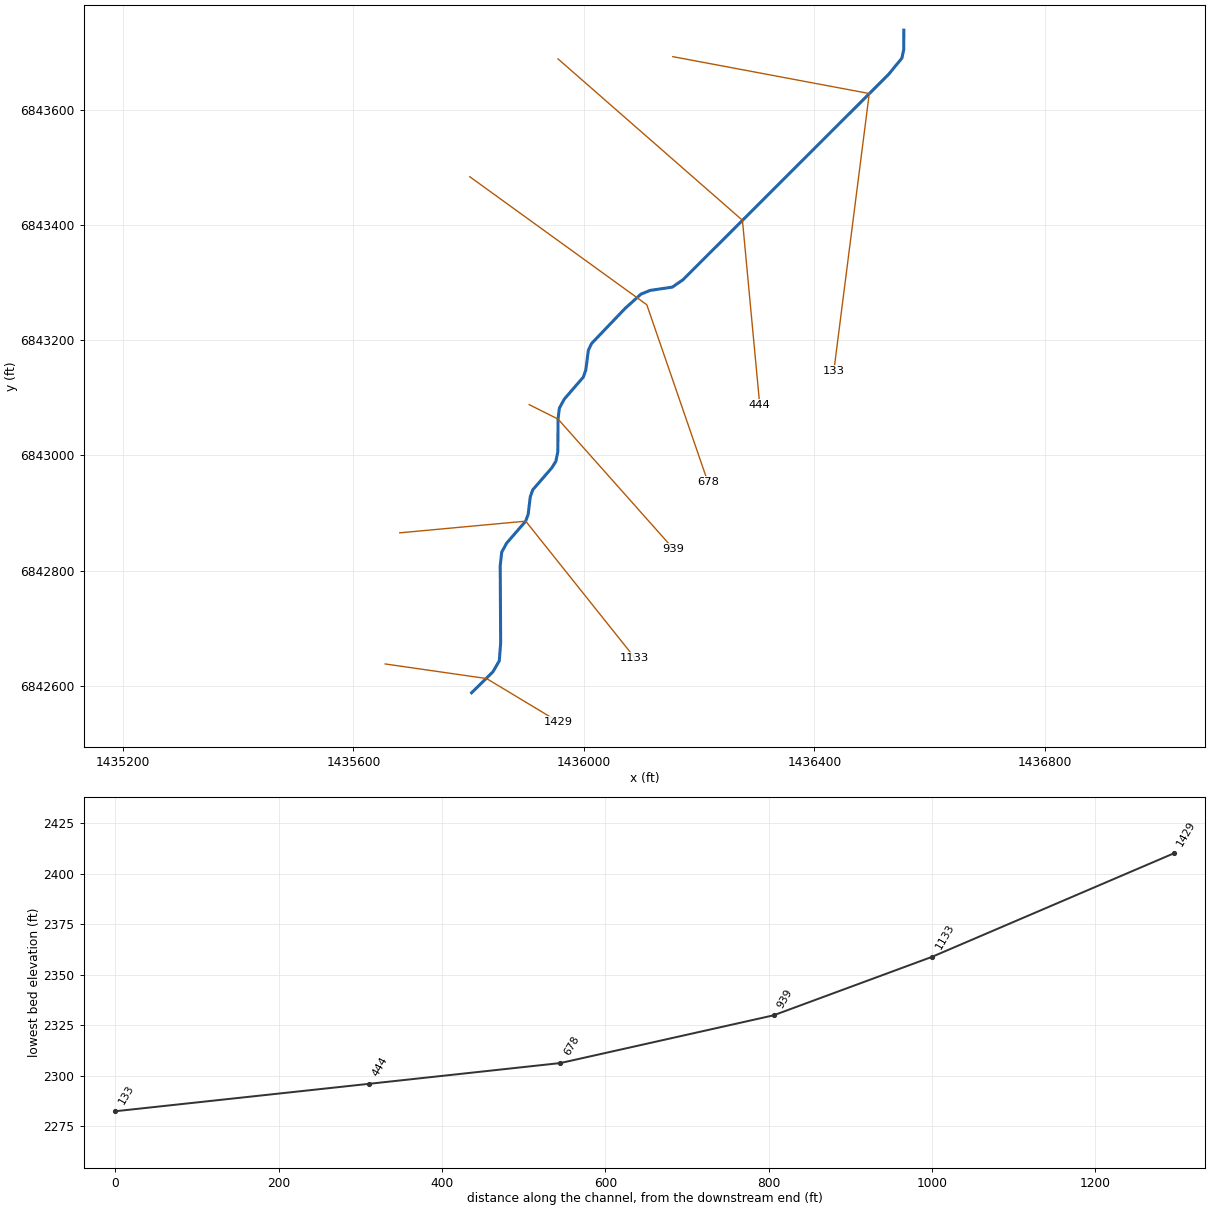
--- Stink Creek Trib1.prj (project) ---

Proj Title=Stink Creek Trib1 Base Level Engineering
Current Plan=p01
Default Exp/Contr=0.3,0.1
English Units
Geom File=g01
Flow File=f01
Plan File=p01
Y Axis Title=Elevation
X Axis Title(PF)=Main Channel Distance
X Axis Title(XS)=Station
BEGIN DESCRIPTION:
Stink Creek Trib1
END DESCRIPTION:
DSS Export Rating Curves= 0
DSS Export Rating Curve Sorted= 0
DSS Export Volume Flow Curves= 0
DXF OffsetX= 0
DXF OffsetY= 0
DXF ScaleX= 1
DXF ScaleY= 10

--- Stink Creek Trib1.p01 (plan) ---

Plan Title=Multiple Run
Short Identifier=Multiple
Geom File=g01
Flow File=f01
Subcritical Flow
K Sum by GR= 0
Std Step Tol= 0.01
Critical Tol= 0.01
Num of Std Step Trials= 20
Max Error Tol= 0.3
Flow Tol Ratio= 0.001
Split Flow NTrial= 30
Split Flow Tol= 0.02
Split Flow Ratio= 0.02
Log Output Level= 0
Friction Slope Method= 1
Unsteady Friction Slope Method= 2
Unsteady Bridges Friction Slope Method= 1
Parabolic Critical Depth
Global Vel Dist=  1 , 1 , 1
Global Log Level= 0
CheckData=True
Encroach Param= -1, 0, 0, 0
BEGIN DESCRIPTION:
Multiple Run
END DESCRIPTION:

--- Stink Creek Trib1.f01 (steady flow) ---

Flow Title=Multiple
Number of Profiles=7
Profile Names=10-year,25-year,50-year,1pct_min,100-year,1pct_plu,500-year
River Rch & RM= Stink Creek Trib,Reach-1,1429
     121     166     204     126     251     500     381
Boundary for River Rch & Prof#=Stink Creek Trib,Reach-1,1
Up Type=0
Dn Type=3
Dn Slope=0.005
Boundary for River Rch & Prof#=Stink Creek Trib,Reach-1,2
Up Type=0
Dn Type=3
Dn Slope=0.005
Boundary for River Rch & Prof#=Stink Creek Trib,Reach-1,3
Up Type=0
Dn Type=3
Dn Slope=0.005
Boundary for River Rch & Prof#=Stink Creek Trib,Reach-1,4
Up Type=0
Dn Type=3
Dn Slope=0.005
Boundary for River Rch & Prof#=Stink Creek Trib,Reach-1,5
Up Type=0
Dn Type=3
Dn Slope=0.005
Boundary for River Rch & Prof#=Stink Creek Trib,Reach-1,6
Up Type=0
Dn Type=3
Dn Slope=0.005
Boundary for River Rch & Prof#=Stink Creek Trib,Reach-1,7
Up Type=0
Dn Type=3
Dn Slope=0.005

--- Stink Creek Trib1.g01 (geometry) ---

Geom Title=Existing Conditions

River Reach=Stink Creek Trib,Reach-1
Reach XY= 30
      1435805.00      6842588.00      1435842.08      6842624.50
      1435853.00      6842643.37      1435855.41      6842674.19
      1435854.64      6842808.15      1435857.24      6842832.07
      1435865.80      6842847.67      1435898.88      6842885.82
      1435903.17      6842897.85      1435906.83      6842928.15
      1435911.11      6842940.18      1435944.16      6842978.35
      1435951.17      6842989.58      1435954.64      6843006.33
      1435954.99      6843063.00      1435957.33      6843082.03
      1435965.84      6843097.65      1435998.86      6843135.83
      1436003.12      6843147.87      1436007.60      6843182.38
      1436013.13      6843194.07      1436071.42      6843255.08
      1436098.93      6843279.85      1436114.79      6843286.30
      1436153.35      6843291.98      1436171.67      6843304.65
      1436528.65      6843661.20      1436551.73      6843689.36
      1436554.93      6843704.37      1436555.00      6843738.00

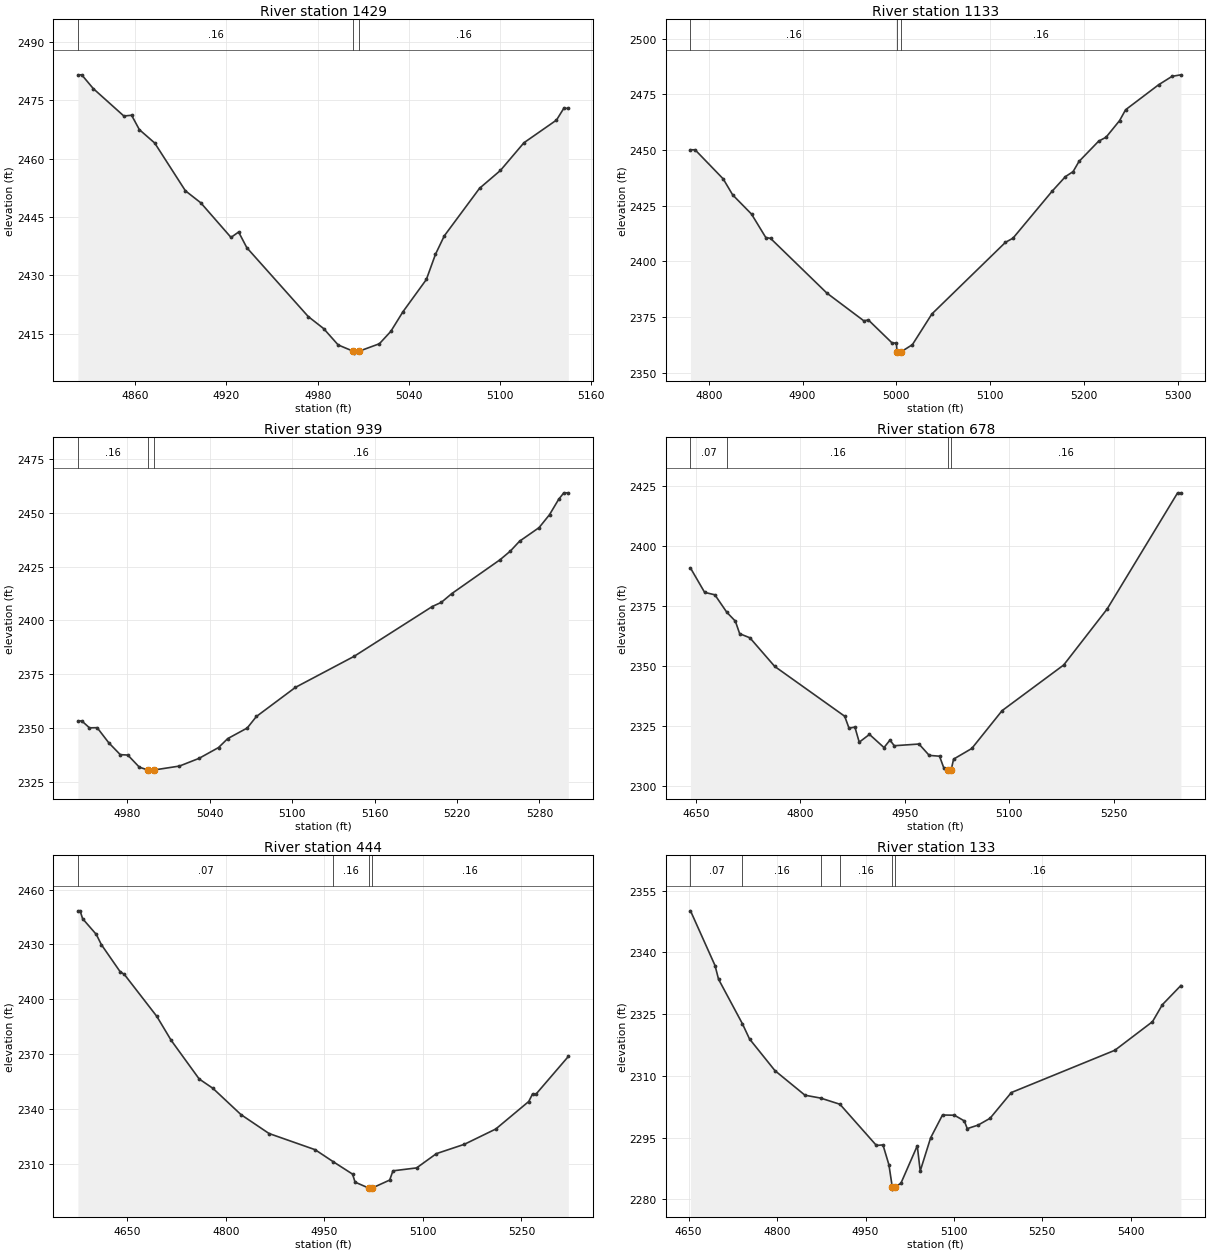
Type RM Length L Ch R = 1,1429,296,296,296
BEGIN DESCRIPTION:
Stink Creek Trib1 2.0
END DESCRIPTION:
XS GIS Cut Line= 3
      1435655.00      6842638.00      1435830.89      6842612.71
      1435955.03      6842537.98
#Sta/Elev= 30
  4822.3 2481.55  4824.8 2481.55  4832.4 2478.01  4852.5 2470.97  4857.6 2471.16
  4862.7 2467.47  4872.8 2464.03  4893.0 2451.75  4903.1 2448.67  4923.0 2439.77
  4928.0 2441.16  4933.4 2437.13  4973.8 2419.44  4983.9 2416.36  4993.5 2412.14
  5003.3 2410.54  5003.6 2410.04  5007.3 2410.54  5020.6 2412.45  5028.1 2415.62
  5036.1 2420.67  5051.5 2428.96  5057.5 2435.44  5063.3 2440.17  5086.5 2452.40
  5100.2 2456.97  5115.7 2464.10  5137.1 2469.92  5141.9 2472.94  5144.9 2472.94
#Mann=3,-1,0
  4822.3    0.16       0  5003.3    0.07       0  5007.3    0.16       0
Bank Sta=5003.3,5007.3
Exp/Cntr=0.3,0.1

Type RM Length L Ch R = 1,1133,194,194,194
BEGIN DESCRIPTION:
Stink Creek Trib1 4478
END DESCRIPTION:
XS GIS Cut Line= 3
      1435680.22      6842865.57      1435898.88      6842885.82
      1436088.17      6842648.58
#Sta/Elev= 30
  4780.4 2450.08  4785.3 2450.08  4815.3 2437.02  4825.4 2429.84  4845.5 2421.23
  4860.7 2410.72  4865.8 2410.33  4925.8 2385.81  4965.2 2373.37  4970.2 2373.70
  4995.5 2363.38  5000.0 2363.38  5000.7 2359.34  5000.9 2358.84  5004.7 2359.34
  5017.1 2362.64  5037.9 2376.42  5116.4 2408.57  5124.4 2410.42  5166.0 2431.43
  5180.4 2438.07  5188.5 2440.28  5194.8 2444.85  5215.7 2453.92  5223.7 2455.73
  5238.1 2463.18  5244.5 2468.04  5279.7 2479.25  5294.1 2483.05  5303.5 2483.72
#Mann=3,-1,0
  4780.4    0.16       0  5000.7    0.07       0  5004.7    0.16       0
Bank Sta=5000.7,5004.7
Exp/Cntr=0.3,0.1

Type RM Length L Ch R = 1,939,261,261,261
BEGIN DESCRIPTION:
Stink Creek Trib1 1.0
END DESCRIPTION:
XS GIS Cut Line= 3
      1435904.99      6843088.00      1435954.99      6843063.00
      1436154.97      6842838.04
#Sta/Elev= 30
  4944.1 2353.27  4946.9 2353.27  4952.5 2350.05  4958.1 2350.12  4966.5 2343.13
  4974.9 2337.58  4980.4 2337.39  4988.8 2331.74  4995.2 2330.41  4995.5 2329.91
  4999.2 2330.41  5018.0 2332.27  5032.2 2335.84  5046.4 2340.87  5053.1 2345.04
  5067.3 2349.97  5074.0 2355.34  5102.4 2368.88  5145.1 2383.32  5202.0 2406.50
  5208.6 2408.45  5216.2 2412.52  5251.3 2428.26  5258.8 2432.29  5265.5 2436.88
  5279.7 2443.20  5287.3 2449.22  5293.9 2456.31  5297.7 2459.39  5301.0 2459.39
#Mann=3,-1,0
  4944.1    0.16       0  4995.2    0.07       0  4999.2    0.16       0
Bank Sta=4995.2,4999.2
Exp/Cntr=0.3,0.1

Type RM Length L Ch R = 1,678,234,234,234
BEGIN DESCRIPTION:
Stink Creek Trib1 4477
END DESCRIPTION:
XS GIS Cut Line= 3
      1435801.77      6843483.60      1436109.02      6843261.40
      1436214.92      6842954.12
#Sta/Elev= 30
  4642.5 2390.90  4662.8 2380.75  4677.5 2379.74  4694.7 2372.44  4706.9 2368.78
  4713.1 2363.54  4727.8 2361.83  4763.4 2349.92  4863.9 2329.16  4870.1 2324.21
  4878.6 2324.62  4884.8 2318.35  4899.5 2321.59  4920.4 2316.10  4928.9 2319.22
  4935.1 2316.87  4970.6 2317.58  4985.3 2312.85  5000.1 2312.51  5006.2 2307.67
  5012.8 2306.79  5013.0 2306.29  5016.8 2306.79  5020.3 2311.29  5046.4 2315.72
  5090.0 2331.50  5178.4 2350.50  5240.8 2373.83  5342.0 2422.22  5346.7 2422.22
#Mann=4,-1,0
  4642.5    0.07       0  4694.7    0.16       0  5012.8    0.07       0
  5016.8    0.16       0
Bank Sta=5012.8,5016.8
Exp/Cntr=0.3,0.1

Type RM Length L Ch R = 1,444,311,311,311
BEGIN DESCRIPTION:
Stink Creek Trib1 2924
END DESCRIPTION:
XS GIS Cut Line= 3
      1435955.01      6843687.99      1436275.00      6843408.00
      1436305.00      6843088.00
#Sta/Elev= 30
  4574.8 2448.42  4578.1 2448.42  4581.9 2444.12  4602.8 2435.49  4610.4 2429.95
  4638.9 2415.16  4645.5 2413.58  4694.9 2390.62  4716.7 2377.53  4759.4 2356.34
  4780.3 2351.23  4823.0 2336.84  4865.7 2326.49  4935.9 2317.62  4963.8 2310.96
  4992.9 2304.25  4996.7 2299.86  5018.1 2296.53  5018.3 2296.03  5022.1 2296.53
  5049.4 2300.99  5054.4 2306.05  5090.4 2307.65  5120.5 2315.46  5163.2 2320.59
  5210.9 2328.94  5261.1 2344.01  5267.0 2348.19  5272.0 2347.98  5321.4 2368.67
#Mann=4,-1,0
  4574.8    0.07       0  4963.8    0.16       0  5018.1    0.07       0
  5022.1    0.16       0
Bank Sta=5018.1,5022.1
Exp/Cntr=0.3,0.1

Type RM Length L Ch R = 1,133,0,0,0
BEGIN DESCRIPTION:
Stink Creek Trib1 4476
END DESCRIPTION:
XS GIS Cut Line= 3
      1436154.15      6843691.96      1436495.10      6843627.96
      1436433.68      6843146.86
#Sta/Elev= 30
  4653.1 2350.13  4694.7 2336.83  4700.7 2333.49  4741.3 2322.63  4753.2 2318.98
  4796.4 2311.26  4847.3 2305.29  4873.9 2304.59  4906.6 2303.09  4968.5 2293.07
  4979.6 2293.21  4989.7 2288.37  4995.4 2282.95  4995.7 2282.45  4999.4 2282.95
  5010.0 2283.86  5037.8 2292.99  5042.8 2286.85  5060.4 2294.90  5080.6 2300.48
  5100.8 2300.42  5117.6 2299.04  5122.6 2297.16  5141.1 2298.03  5161.3 2299.68
  5197.4 2305.94  5373.0 2316.22  5436.8 2323.17  5453.6 2327.31  5485.0 2331.97
#Mann=6,-1,0
  4653.1    0.07       0  4741.3    0.16       0  4873.9    0.07       0
  4906.6    0.16       0  4995.4    0.07       0  4999.4    0.16       0
Bank Sta=4995.4,4999.4
Exp/Cntr=0.3,0.1

Chan Stop Cuts=-1