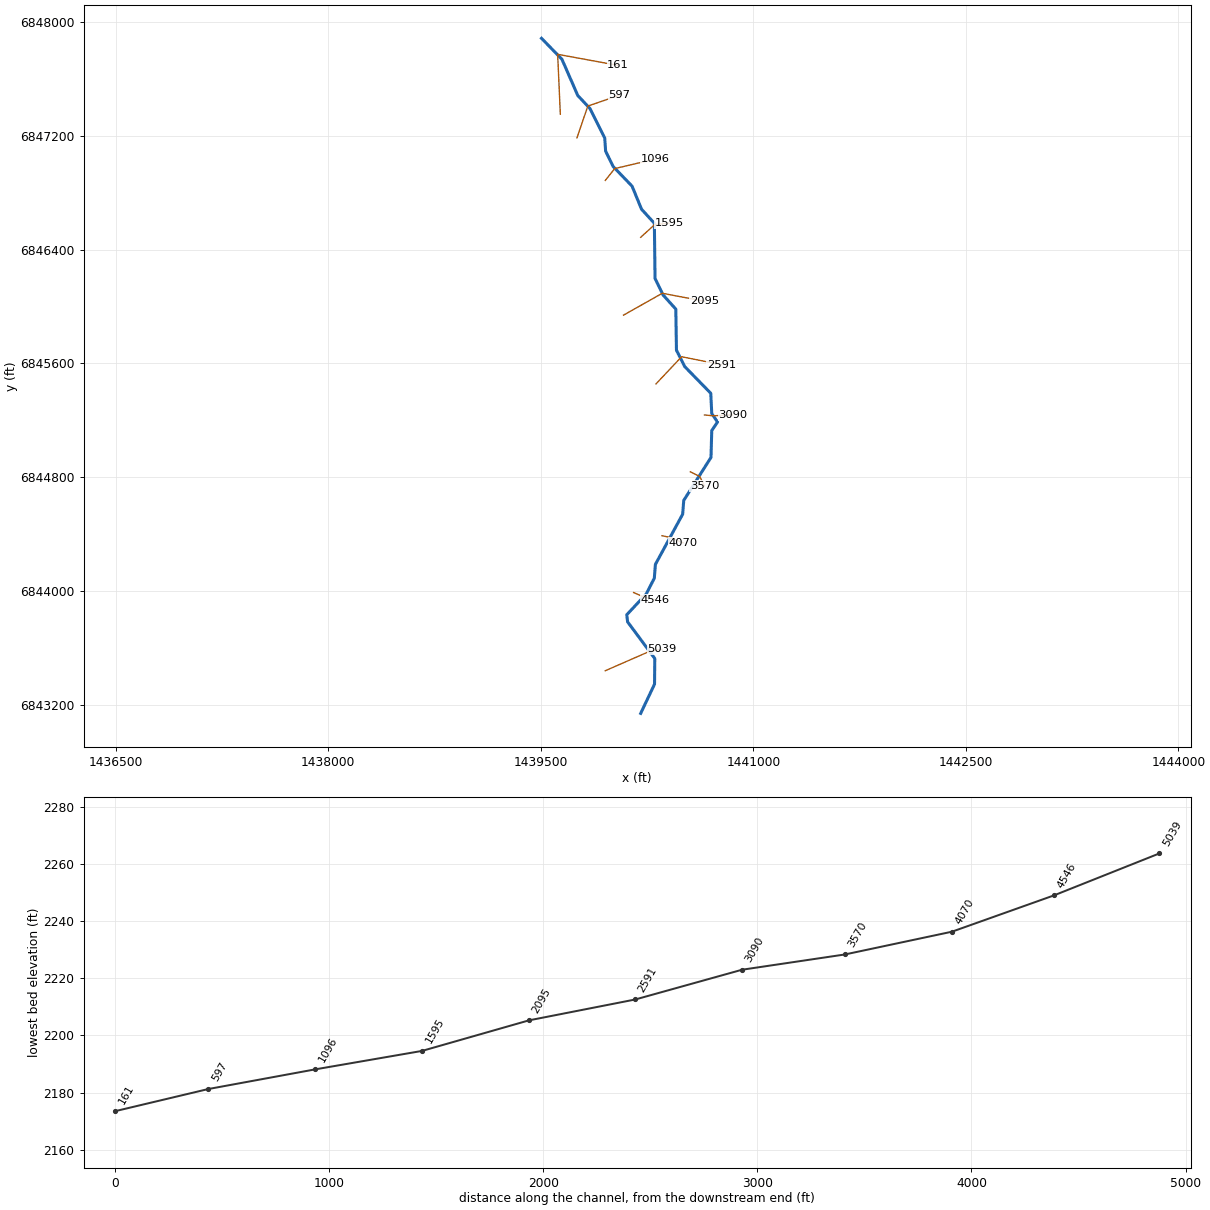
--- Stink Creek Trib2.prj (project) ---

Proj Title=Stink Creek Trib2 Base Level Engineering
Current Plan=p01
Default Exp/Contr=0.3,0.1
English Units
Geom File=g01
Flow File=f01
Plan File=p01
Y Axis Title=Elevation
X Axis Title(PF)=Main Channel Distance
X Axis Title(XS)=Station
BEGIN DESCRIPTION:
Stink Creek Trib2
END DESCRIPTION:
DSS Export Rating Curves= 0
DSS Export Rating Curve Sorted= 0
DSS Export Volume Flow Curves= 0
DXF OffsetX= 0
DXF OffsetY= 0
DXF ScaleX= 1
DXF ScaleY= 10

--- Stink Creek Trib2.p01 (plan) ---

Plan Title=Multiple Run
Short Identifier=Multiple
Geom File=g01
Flow File=f01
Subcritical Flow
K Sum by GR= 0
Std Step Tol= 0.01
Critical Tol= 0.01
Num of Std Step Trials= 20
Max Error Tol= 0.3
Flow Tol Ratio= 0.001
Split Flow NTrial= 30
Split Flow Tol= 0.02
Split Flow Ratio= 0.02
Log Output Level= 0
Friction Slope Method= 1
Unsteady Friction Slope Method= 2
Unsteady Bridges Friction Slope Method= 1
Parabolic Critical Depth
Global Vel Dist=  1 , 1 , 1
Global Log Level= 0
CheckData=True
Encroach Param= -1, 0, 0, 0
BEGIN DESCRIPTION:
Multiple Run
END DESCRIPTION:

--- Stink Creek Trib2.f01 (steady flow) ---

Flow Title=Multiple
Program Version=4.10
Number of Profiles= 7
Profile Names=10-year,25-year,50-year,1pct_min,100-year,1pct_plu,500-year
River Rch & RM=Stink Creek Trib,Reach-1         ,5039
     478     710     916     589    1176    2346    1959
Boundary for River Rch & Prof#=Stink Creek Trib,Reach-1         , 1
Up Type= 0
Dn Type= 3
Dn Slope=0.017
Boundary for River Rch & Prof#=Stink Creek Trib,Reach-1         , 2
Up Type= 0
Dn Type= 3
Dn Slope=0.017
Boundary for River Rch & Prof#=Stink Creek Trib,Reach-1         , 3
Up Type= 0
Dn Type= 3
Dn Slope=0.017
Boundary for River Rch & Prof#=Stink Creek Trib,Reach-1         , 4
Up Type= 0
Dn Type= 3
Dn Slope=0.017
Boundary for River Rch & Prof#=Stink Creek Trib,Reach-1         , 5
Up Type= 0
Dn Type= 3
Dn Slope=0.017
Boundary for River Rch & Prof#=Stink Creek Trib,Reach-1         , 6
Up Type= 0
Dn Type= 3
Dn Slope=0.017
Boundary for River Rch & Prof#=Stink Creek Trib,Reach-1         , 7
Up Type= 0
Dn Type= 3
Dn Slope=0.017
DSS Import GetInterval= 0
DSS Import GetPeak= 0
DSS Import FillOption= 0

--- Stink Creek Trib2.g01 (geometry) ---

Geom Title=Existing Conditions

River Reach=Stink Creek Trib,Reach-1
Reach XY= 30
      1440205.00      6843138.00      1440302.65      6843343.52
      1440304.46      6843524.14      1440112.48      6843781.96
      1440106.58      6843831.95      1440244.24      6843978.32
      1440301.17      6844089.58      1440308.83      6844186.42
      1440501.17      6844539.58      1440508.83      6844636.42
      1440701.25      6844939.55      1440706.55      6845128.41
      1440747.44      6845188.00      1440706.56      6845247.60
      1440699.53      6845390.45      1440515.76      6845578.32
      1440457.35      6845693.52      1440452.82      6845982.55
      1440363.16      6846081.95      1440306.20      6846198.50
      1440301.45      6846586.53      1440210.85      6846685.71
      1440144.23      6846847.68      1440010.83      6846985.70
      1439957.33      6847093.97      1439951.17      6847186.42
      1439846.84      6847394.05      1439760.85      6847485.71
      1439649.17      6847740.30      1439505.00      6847888.00

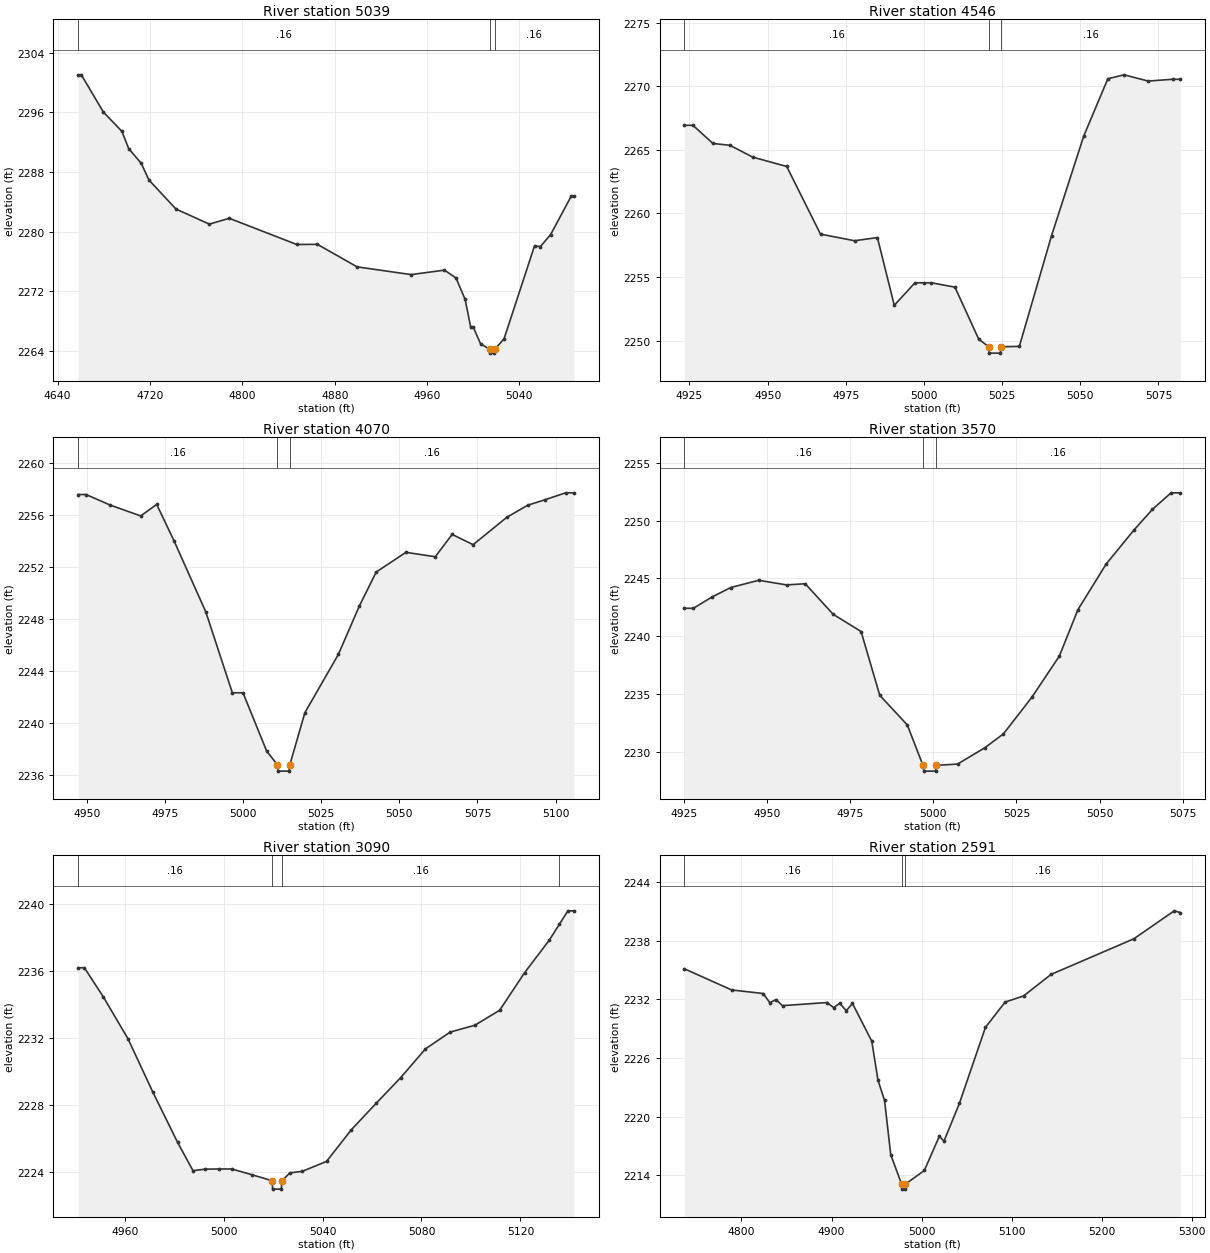
Type RM Length L Ch R = 1,5039,493,493,493
BEGIN DESCRIPTION:
Stink Creek Trib2 9.0
END DESCRIPTION:
XS GIS Cut Line= 3
      1439954.98      6843437.99      1440268.65      6843574.80
      1440355.04      6843588.01
#Sta/Elev= 30
  4657.8 2301.04  4660.5 2301.04  4679.6 2296.05  4695.7 2293.45  4701.5 2291.16
  4712.4 2289.17  4719.1 2286.93  4742.5 2283.04  4771.4 2281.02  4788.7 2281.80
  4847.1 2278.29  4865.0 2278.31  4899.4 2275.29  4946.2 2274.25  4975.1 2274.85
  4985.1 2273.80  4993.0 2270.92  4997.8 2267.23  5000.0 2267.23  5006.4 2264.96
  5014.5 2264.22  5014.8 2263.72  5018.3 2263.72  5018.5 2264.22  5026.7 2265.63
  5053.1 2278.09  5058.2 2278.01  5067.1 2279.62  5084.8 2284.74  5087.4 2284.74
#Mann=3,-1,0
  4657.8    0.16       0  5014.5    0.07       0  5018.5    0.16       0
Bank Sta=5014.5,5018.5
Exp/Cntr=0.3,0.1

Type RM Length L Ch R = 1,4546,476,476,476
BEGIN DESCRIPTION:
Stink Creek Trib2 8.0
END DESCRIPTION:
XS GIS Cut Line= 3
      1440154.98      6843988.01      1440225.39      6843957.84
      1440304.95      6843938.01
#Sta/Elev= 27
  4923.4 2266.93  4926.1 2266.93  4932.5 2265.50  4937.9 2265.36  4945.2 2264.43
  4956.1 2263.69  4966.9 2258.37  4977.8 2257.85  4985.1 2258.10  4990.5 2252.77
  4997.1 2254.54  5000.0 2254.54  5002.4 2254.54  5009.9 2254.20  5017.5 2250.11
  5020.7 2249.51  5020.9 2249.01  5024.4 2249.01  5024.7 2249.51  5030.5 2249.54
  5040.8 2258.25  5051.1 2266.09  5058.8 2270.59  5064.0 2270.90  5071.7 2270.41
  5079.5 2270.55  5082.0 2270.55
#Mann=3,-1,0
  4923.4    0.16       0  5020.7    0.07       0  5024.7    0.16       0
Bank Sta=5020.7,5024.7
Exp/Cntr=0.3,0.1

Type RM Length L Ch R = 1,4070,500,500,500
BEGIN DESCRIPTION:
Stink Creek Trib2 7.0
END DESCRIPTION:
XS GIS Cut Line= 3
      1440355.05      6844387.99      1440406.65      6844377.31
      1440504.99      6844338.00
#Sta/Elev= 27
  4947.3 2257.60  4949.8 2257.60  4957.5 2256.79  4967.3 2255.95  4972.4 2256.84
  4977.9 2254.06  4988.1 2248.57  4996.6 2242.34  5000.0 2242.34  5007.6 2237.84
  5011.0 2236.81  5011.2 2236.31  5014.7 2236.31  5015.0 2236.81  5019.8 2240.81
  5030.5 2245.29  5037.2 2249.01  5042.6 2251.63  5052.1 2253.15  5061.5 2252.81
  5066.9 2254.53  5073.6 2253.74  5084.4 2255.85  5091.1 2256.78  5096.5 2257.19
  5103.2 2257.73  5105.9 2257.73
#Mann=3,-1,0
  4947.3    0.16       0  5011.0    0.07       0  5015.0    0.16       0
Bank Sta=5011,5015
Exp/Cntr=0.3,0.1

Type RM Length L Ch R = 1,3570,480,480,480
BEGIN DESCRIPTION:
Stink Creek Trib2 6.0
END DESCRIPTION:
XS GIS Cut Line= 3
      1440555.04      6844837.98      1440621.96      6844804.55
      1440655.00      6844738.00
#Sta/Elev= 26
  4925.2 2242.42  4927.9 2242.42  4933.5 2243.40  4939.1 2244.21  4947.5 2244.84
  4955.9 2244.44  4961.5 2244.54  4969.9 2241.90  4978.3 2240.41  4983.9 2234.90
  4992.2 2232.33  4996.9 2228.84  4997.2 2228.34  5000.7 2228.34  5000.9 2228.84
  5007.3 2228.95  5015.5 2230.36  5021.1 2231.56  5029.6 2234.71  5037.9 2238.28
  5043.5 2242.30  5052.0 2246.25  5060.3 2249.17  5065.9 2250.97  5071.5 2252.40
  5074.3 2252.40
#Mann=3,-1,0
  4925.2    0.16       0  4996.9    0.07       0  5000.9    0.16       0
Bank Sta=4996.9,5000.9
Exp/Cntr=0.3,0.1

Type RM Length L Ch R = 1,3090,499,499,499
BEGIN DESCRIPTION:
Stink Creek Trib2 5.0
END DESCRIPTION:
XS GIS Cut Line= 3
      1440654.99      6845238.00      1440713.46      6845231.82
      1440855.02      6845238.00
#Sta/Elev= 30
  4941.2 2236.18  4943.7 2236.18  4951.3 2234.46  4961.3 2231.96  4971.4 2228.77
  4981.4 2225.78  4987.6 2224.10  4992.6 2224.19  4998.3 2224.20  5003.3 2224.20
  5011.6 2223.85  5019.6 2223.50  5019.8 2223.00  5023.3 2223.00  5023.6 2223.50
  5026.8 2223.97  5031.8 2224.06  5041.6 2224.65  5051.6 2226.53  5061.6 2228.10
  5071.6 2229.64  5081.6 2231.35  5091.6 2232.35  5101.6 2232.76  5111.6 2233.65
  5121.7 2235.89  5131.7 2237.83  5135.7 2238.76  5139.2 2239.57  5141.7 2239.57
#Mann=4,-1,0
  4941.2    0.16       0  5019.6    0.07       0  5023.6    0.16       0
  5135.7    0.07       0
Bank Sta=5019.6,5023.6
Exp/Cntr=0.3,0.1

Type RM Length L Ch R = 1,2591,496,496,496
BEGIN DESCRIPTION:
Stink Creek Trib2 4.0
END DESCRIPTION:
XS GIS Cut Line= 3
      1440312.90      6845456.25      1440493.84      6845647.52
      1440775.83      6845591.51
#Sta/Elev= 30
  4736.7 2235.14  4789.0 2232.98  4824.2 2232.61  4831.5 2231.67  4838.3 2231.99
  4845.6 2231.37  4895.0 2231.69  4902.3 2231.17  4909.1 2231.60  4916.4 2230.86
  4923.3 2231.59  4944.7 2227.74  4951.6 2223.74  4958.9 2221.67  4965.8 2216.11
  4977.9 2213.08  4978.2 2212.58  4981.7 2212.58  4981.9 2213.08  5003.1 2214.49
  5019.8 2218.00  5024.9 2217.49  5042.0 2221.35  5071.0 2229.15  5092.9 2231.74
  5113.3 2232.36  5143.9 2234.57  5235.7 2238.21  5280.7 2241.08  5287.5 2240.90
#Mann=3,-1,0
  4736.7    0.16       0  4977.9    0.07       0  4981.9    0.16       0
Bank Sta=4977.9,4981.9
Exp/Cntr=0.3,0.1

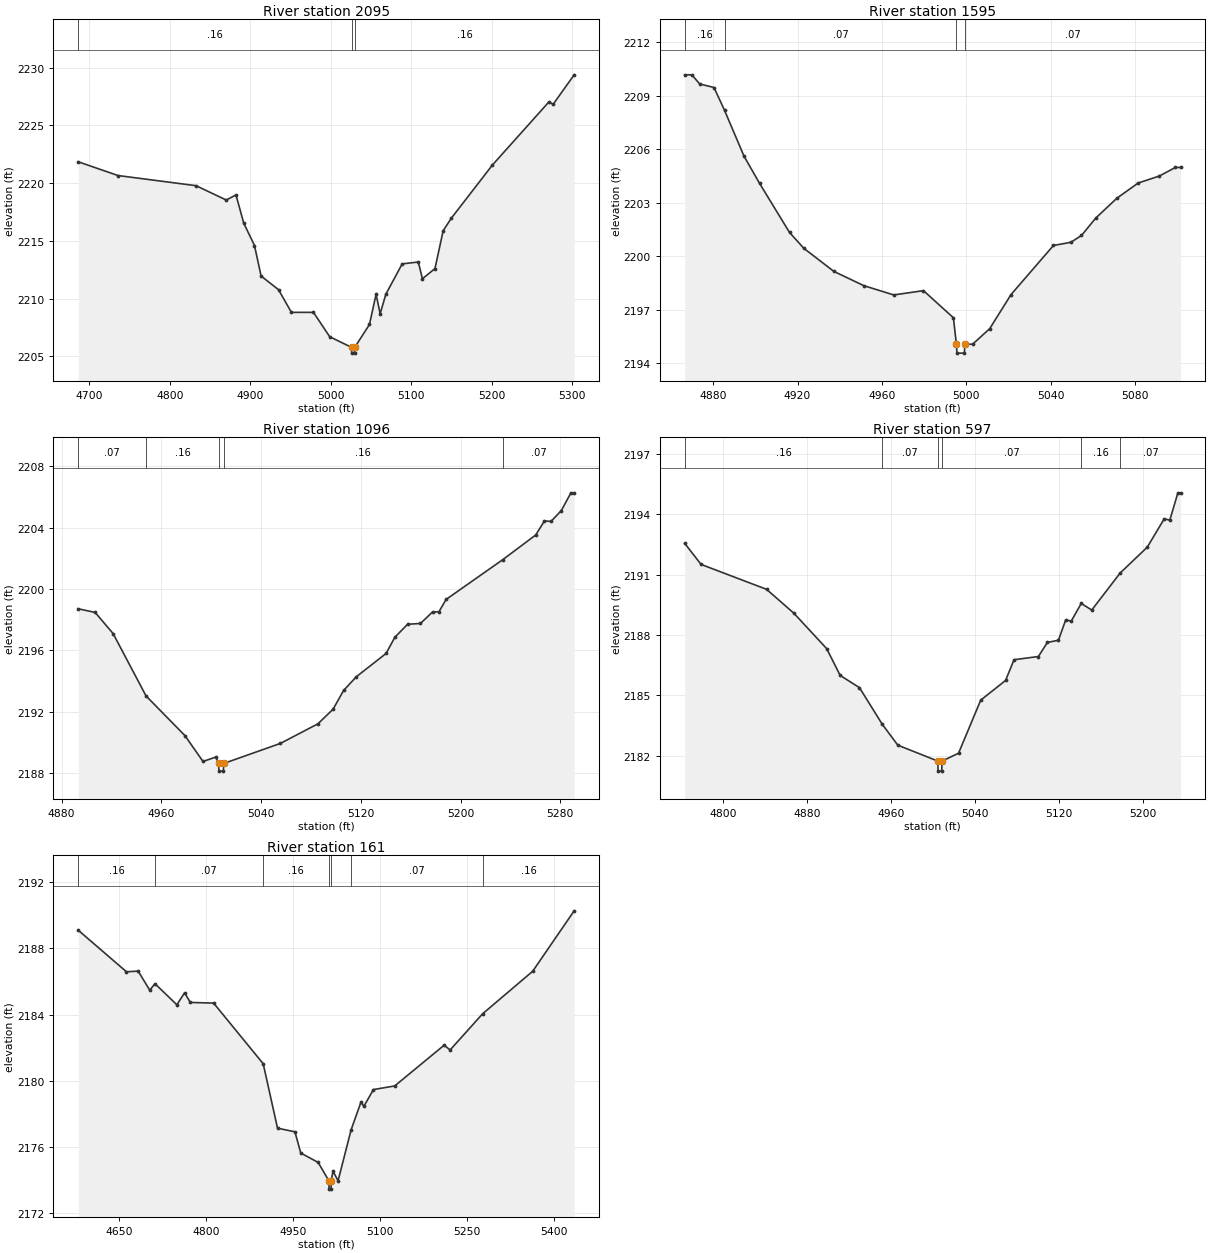
Type RM Length L Ch R = 1,2095,500,500,500
BEGIN DESCRIPTION:
Stink Creek Trib2 3.0
END DESCRIPTION:
XS GIS Cut Line= 3
      1440083.98      6845940.44      1440357.50      6846094.04
      1440654.97      6846038.01
#Sta/Elev= 30
  4686.3 2221.85  4735.7 2220.66  4832.7 2219.78  4870.3 2218.54  4882.4 2218.98
  4892.0 2216.54  4905.4 2214.60  4913.6 2211.96  4935.3 2210.77  4951.3 2208.81
  4978.7 2208.81  4998.9 2206.70  5026.0 2205.78  5026.2 2205.28  5029.7 2205.28
  5030.0 2205.78  5048.3 2207.76  5056.5 2210.37  5061.6 2208.69  5068.7 2210.39
  5089.0 2213.01  5109.0 2213.17  5114.1 2211.72  5129.7 2212.60  5139.9 2215.88
  5150.1 2216.97  5201.0 2221.56  5271.4 2227.04  5276.5 2226.82  5302.7 2229.38
#Mann=3,-1,0
  4686.3    0.16       0  5026.0    0.07       0  5030.0    0.16       0
Bank Sta=5026,5030
Exp/Cntr=0.3,0.1

Type RM Length L Ch R = 1,1595,499,499,499
BEGIN DESCRIPTION:
Stink Creek Trib2 2.0
END DESCRIPTION:
XS GIS Cut Line= 3
      1440204.97      6846487.97      1440303.95      6846577.56
      1440405.01      6846588.00
#Sta/Elev= 30
  4866.5 2210.16  4869.9 2210.16  4873.6 2209.65  4880.4 2209.45  4885.4 2208.17
  4894.6 2205.61  4902.0 2204.08  4916.2 2201.33  4923.0 2200.44  4937.2 2199.15
  4951.4 2198.35  4965.6 2197.83  4979.7 2198.07  4993.9 2196.55  4995.3 2195.07
  4995.6 2194.57  4999.1 2194.57  4999.3 2195.07  5003.0 2195.07  5011.1 2195.94
  5021.2 2197.85  5041.3 2200.60  5049.6 2200.78  5054.6 2201.16  5061.4 2202.14
  5071.4 2203.25  5081.5 2204.10  5091.5 2204.49  5099.1 2204.97  5101.6 2204.97
#Mann=4,-1,0
  4866.5    0.16       0  4885.4    0.07       0  4995.3    0.07       0
  4999.3    0.07       0
Bank Sta=4995.3,4999.3
Exp/Cntr=0.3,0.1

Type RM Length L Ch R = 1,1096,499,499,499
BEGIN DESCRIPTION:
Stink Creek Trib2 1.0
END DESCRIPTION:
XS GIS Cut Line= 3
      1439955.00      6846888.00      1440021.64      6846971.32
      1440305.00      6847038.00
#Sta/Elev= 30
  4893.3 2198.71  4906.9 2198.47  4921.3 2197.09  4947.7 2193.02  4978.9 2190.43
  4993.4 2188.74  5003.7 2189.03  5006.0 2188.61  5006.2 2188.11  5009.7 2188.11
  5010.0 2188.61  5055.5 2189.92  5085.6 2191.20  5097.8 2192.16  5106.2 2193.38
  5116.5 2194.28  5140.2 2195.79  5147.3 2196.85  5157.5 2197.70  5167.8 2197.75
  5177.5 2198.50  5182.6 2198.51  5188.4 2199.32  5233.9 2201.92  5260.3 2203.53
  5267.3 2204.45  5272.5 2204.41  5280.8 2205.12  5288.5 2206.28  5291.1 2206.28
#Mann=5,-1,0
  4893.3    0.07       0  4947.7    0.16       0  5006.0    0.07       0
  5010.0    0.16       0  5233.9    0.07       0
Bank Sta=5006,5010
Exp/Cntr=0.3,0.1

Type RM Length L Ch R = 1,597,436,436,436
BEGIN DESCRIPTION:
Stink Creek Trib2 2679
END DESCRIPTION:
XS GIS Cut Line= 3
      1439755.01      6847188.02      1439831.94      6847411.45
      1440054.97      6847487.99
#Sta/Elev= 30
  4763.7 2192.56  4779.3 2191.51  4841.7 2190.27  4867.7 2189.08  4898.9 2187.32
  4911.7 2185.99  4930.1 2185.38  4951.8 2183.56  4966.6 2182.52  5004.7 2181.73
  5004.9 2181.23  5008.4 2181.23  5008.7 2181.73  5024.4 2182.12  5045.5 2184.76
  5069.2 2185.74  5077.2 2186.77  5100.4 2186.93  5109.0 2187.63  5119.5 2187.74
  5126.4 2188.75  5131.7 2188.69  5141.2 2189.57  5151.2 2189.24  5178.2 2191.08
  5204.1 2192.37  5220.2 2193.78  5225.5 2193.71  5233.2 2195.07  5235.8 2195.07
#Mann=6,-1,0
  4763.7    0.16       0  4951.8    0.07       0  5004.7    0.07       0
  5008.7    0.07       0  5141.2    0.16       0  5178.2    0.07       0
Bank Sta=5004.7,5008.7
Exp/Cntr=0.3,0.1

Type RM Length L Ch R = 1,161,0,0,0
BEGIN DESCRIPTION:
Stink Creek Trib2 4291
END DESCRIPTION:
XS GIS Cut Line= 3
      1439637.68      6847354.85      1439618.84      6847775.59
      1440045.30      6847697.60
#Sta/Elev= 30
  4579.8 2189.09  4663.0 2186.58  4683.1 2186.62  4703.1 2185.47  4712.1 2185.86
  4749.8 2184.59  4763.1 2185.31  4773.1 2184.73  4813.2 2184.69  4898.6 2181.03
  4923.3 2177.14  4953.3 2176.92  4963.3 2175.64  4993.4 2175.07  5011.8 2173.96
  5012.1 2173.46  5015.6 2173.46  5015.8 2173.96  5018.9 2174.55  5027.6 2173.96
  5050.2 2177.05  5067.1 2178.71  5072.1 2178.46  5088.6 2179.47  5125.3 2179.69
  5210.5 2182.15  5220.7 2181.86  5276.9 2184.05  5363.0 2186.61  5434.5 2190.26
#Mann=7,-1,0
  4579.8    0.16       0  4712.1    0.07       0  4898.6    0.16       0
  5011.8    0.07       0  5015.8    0.16       0  5050.2    0.07       0
  5276.9    0.16       0
Bank Sta=5011.8,5015.8
Exp/Cntr=0.3,0.1

Chan Stop Cuts=-1