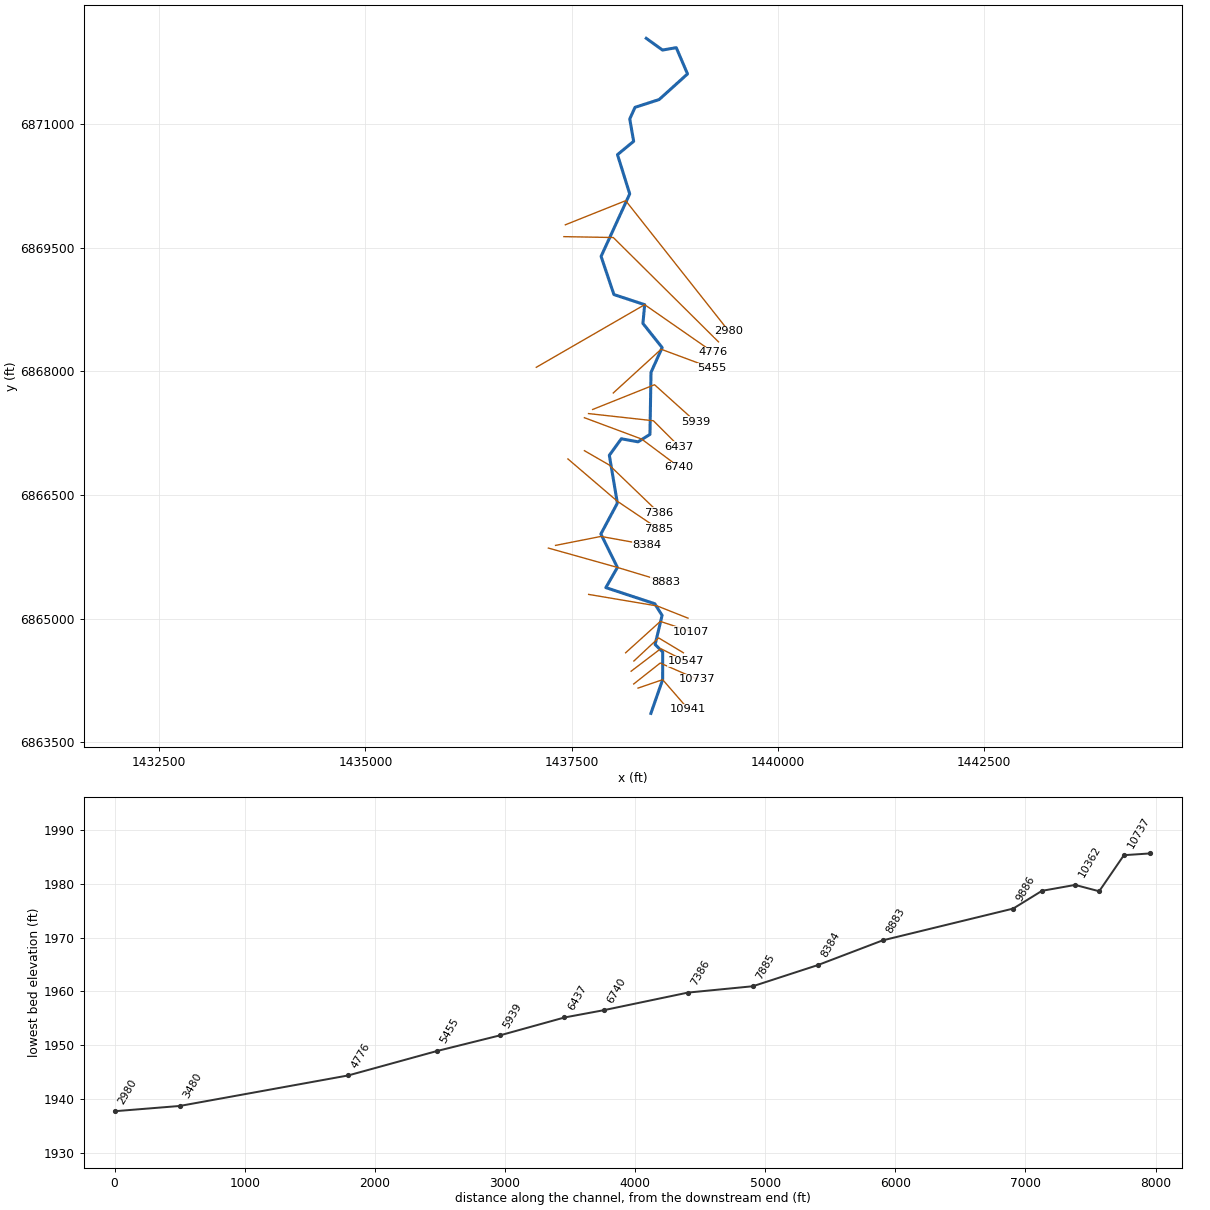
--- Stink Creek Trib3.prj (project) ---

Proj Title=Stink Creek Trib3 Base Level Engineering
Current Plan=p01
Default Exp/Contr=0.3,0.1
English Units
Geom File=g01
Flow File=f01
Plan File=p01
BEGIN DESCRIPTION:
Stink Creek Trib3
END DESCRIPTION:

--- Stink Creek Trib3.p01 (plan) ---

Plan Title=Multiple Run
Short Identifier=Multiple
Geom File=g01
Flow File=f01
Subcritical Flow
K Sum by GR= 0
Std Step Tol= 0.01
Critical Tol= 0.01
Num of Std Step Trials= 20
Max Error Tol= 0.3
Flow Tol Ratio= 0.001
Split Flow NTrial= 30
Split Flow Tol= 0.02
Split Flow Ratio= 0.02
Log Output Level= 0
Friction Slope Method= 1
Unsteady Friction Slope Method= 2
Unsteady Bridges Friction Slope Method= 1
Parabolic Critical Depth
Global Vel Dist=  1 , 1 , 1
Global Log Level= 0
CheckData=True
Encroach Param= -1, 0, 0, 0
BEGIN DESCRIPTION:
Multiple Run
END DESCRIPTION:

--- Stink Creek Trib3.f01 (steady flow) ---

Flow Title=Multiple
Number of Profiles=7
Profile Names=10-year,25-year,50-year,1pct_min,100-year,1pct_plu,500-year
River Rch & RM= Stink Creek Trib,Reach-1,10941
     238     332     409     250     500     997     756
River Rch & RM= Stink Creek Trib,Reach-1,2980
     269     376     464     285     569    1135     865
Boundary for River Rch & Prof#=Stink Creek Trib,Reach-1,1
Up Type=0
Dn Type=3
Dn Slope=0.005
Boundary for River Rch & Prof#=Stink Creek Trib,Reach-1,2
Up Type=0
Dn Type=3
Dn Slope=0.005
Boundary for River Rch & Prof#=Stink Creek Trib,Reach-1,3
Up Type=0
Dn Type=3
Dn Slope=0.005
Boundary for River Rch & Prof#=Stink Creek Trib,Reach-1,4
Up Type=0
Dn Type=3
Dn Slope=0.005
Boundary for River Rch & Prof#=Stink Creek Trib,Reach-1,5
Up Type=0
Dn Type=3
Dn Slope=0.005
Boundary for River Rch & Prof#=Stink Creek Trib,Reach-1,6
Up Type=0
Dn Type=3
Dn Slope=0.005
Boundary for River Rch & Prof#=Stink Creek Trib,Reach-1,7
Up Type=0
Dn Type=3
Dn Slope=0.005

--- Stink Creek Trib3.g01 (geometry) ---

Geom Title=Existing Conditions

River Reach=Stink Creek Trib,Reach-1
Reach XY= 30
      1438461.04      6863852.96      1438603.58      6864261.81
      1438604.10      6864597.41      1438512.26      6864687.70
      1438596.77      6865041.23      1438507.68      6865182.58
      1437915.02      6865377.95      1438055.10      6865622.64
      1437854.49      6866027.83      1438054.46      6866401.86
      1437957.24      6866982.07      1438102.54      6867182.55
      1438305.01      6867145.53      1438449.58      6867235.32
      1438462.56      6867988.00      1438597.71      6868288.09
      1438364.31      6868581.34      1438385.90      6868808.51
      1438012.85      6868931.19      1437857.14      6869393.97
      1438204.33      6870151.91      1438056.03      6870627.57
      1438251.96      6870789.42      1438204.70      6871060.85
      1438268.61      6871201.24      1438561.19      6871295.83
      1438905.20      6871606.41      1438768.66      6871924.81
      1438601.68      6871896.04      1438405.00      6872038.00

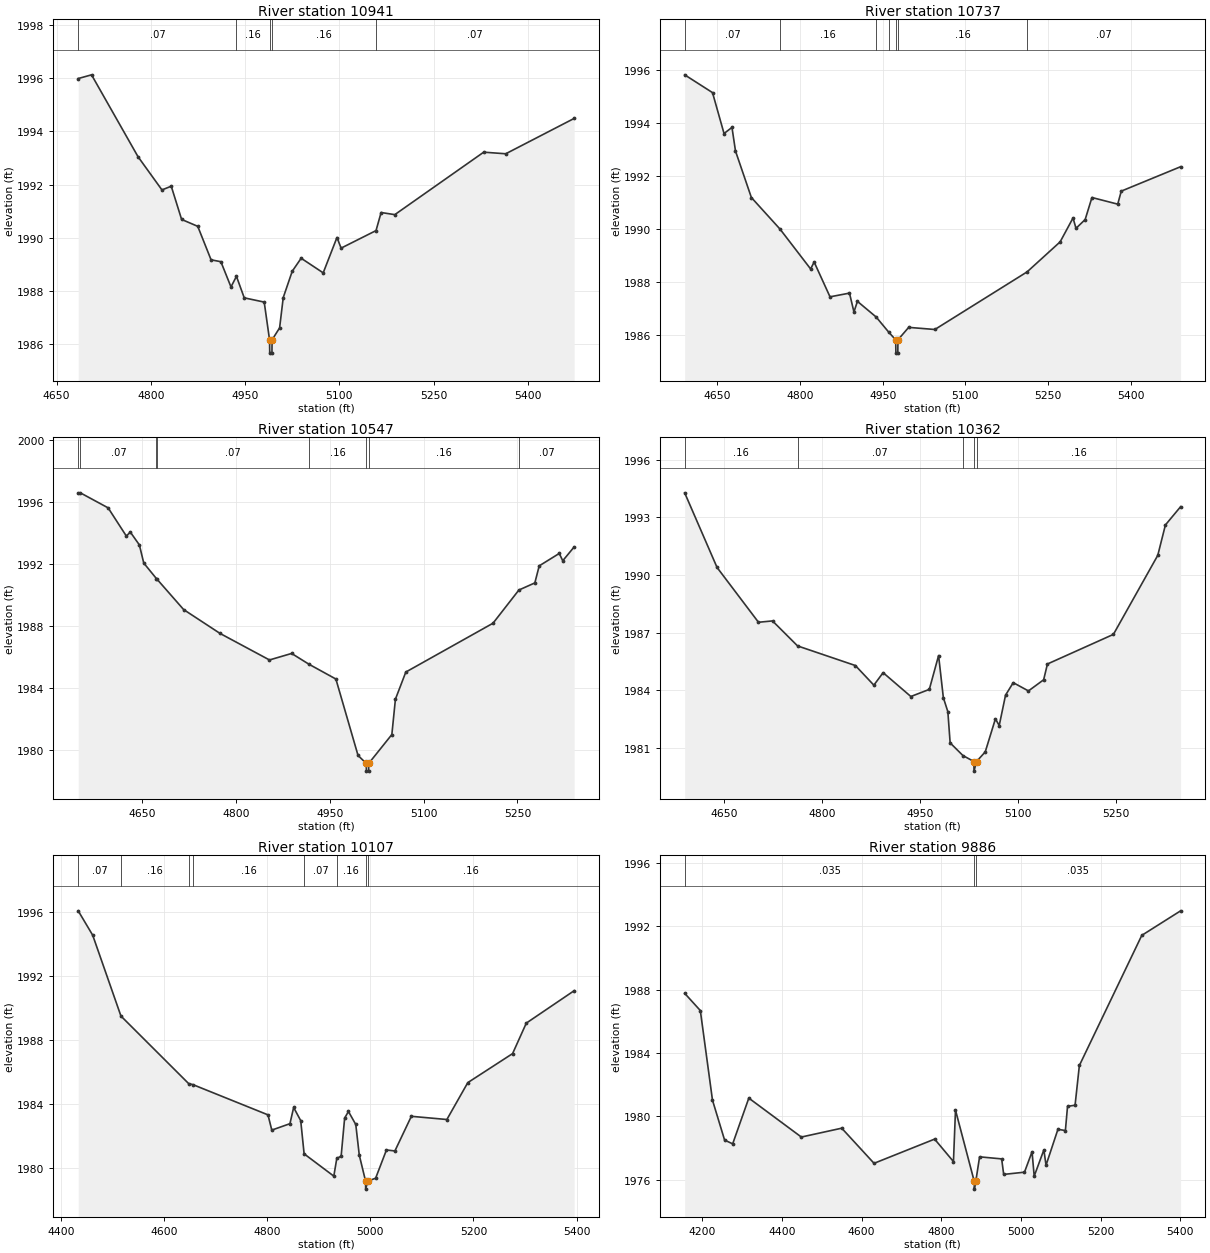
Type RM Length L Ch R = 1,10941,204,204,204
BEGIN DESCRIPTION:
Stink Creek Trib3 4218
END DESCRIPTION:
XS GIS Cut Line= 3
      1438304.96      6864159.38      1438603.58      6864261.81
      1438914.34      6863904.17
#Sta/Elev= 30
  4684.3 1995.99  4705.5 1996.13  4779.5 1993.05  4817.6 1991.80  4832.4 1991.94
  4848.9 1990.69  4874.6 1990.43  4895.8 1989.17  4911.4 1989.10  4927.5 1988.15
  4936.2 1988.55  4948.6 1987.74  4980.4 1987.58  4988.9 1986.16  4989.2 1985.66
  4992.7 1985.66  4992.9 1986.16  5004.9 1986.61  5010.7 1987.75  5025.0 1988.74
  5039.2 1989.23  5074.3 1988.68  5096.2 1990.01  5102.8 1989.61  5158.4 1990.27
  5166.5 1990.95  5188.3 1990.87  5329.8 1993.22  5364.9 1993.16  5473.8 1994.49
#Mann=5,-1,0
  4684.3    0.07       0  4936.2    0.16       0  4988.9    0.07       0
  4992.9    0.16       0  5158.4    0.07       0
Bank Sta=4988.9,4992.9
Exp/Cntr=0.3,0.1

Type RM Length L Ch R = 1,10737,190,190,190
BEGIN DESCRIPTION:
Stink Creek Trib3 4217
END DESCRIPTION:
XS GIS Cut Line= 3
      1438252.84      6864209.70      1438574.06      6864463.20
      1439023.73      6864267.02
#Sta/Elev= 30
  4590.8 1995.81  4641.3 1995.14  4662.2 1993.60  4676.6 1993.83  4683.0 1992.94
  4711.8 1991.19  4763.8 1990.00  4819.3 1988.50  4825.7 1988.76  4854.5 1987.45
  4889.8 1987.59  4897.9 1986.88  4904.2 1987.28  4938.2 1986.69  4961.4 1986.11
  4973.7 1985.83  4974.0 1985.33  4977.5 1985.33  4977.7 1985.83  4997.2 1986.30
  5044.7 1986.22  5212.1 1988.39  5272.0 1989.52  5295.4 1990.42  5300.8 1990.03
  5317.4 1990.36  5329.7 1991.19  5376.5 1990.94  5382.9 1991.43  5490.6 1992.35
#Mann=7,-1,0
  4590.8    0.07       0  4763.8    0.16       0  4938.2    0.07       0
  4961.4    0.16       0  4973.7    0.07       0  4977.7    0.16       0
  5212.1    0.07       0
Bank Sta=4973.7,4977.7
Exp/Cntr=0.3,0.1

Type RM Length L Ch R = 1,10547,185,185,185
BEGIN DESCRIPTION:
Stink Creek Trib3 4216
END DESCRIPTION:
XS GIS Cut Line= 3
      1438221.67      6864364.27      1438580.93      6864637.90
      1438884.81      6864484.05
#Sta/Elev= 30
  4548.4 1996.57  4551.8 1996.57  4596.2 1995.60  4625.3 1993.78  4631.6 1994.04
  4646.1 1993.21  4653.1 1992.04  4673.3 1991.04  4673.6 1991.03  4716.8 1989.04
  4775.0 1987.50  4853.9 1985.79  4889.3 1986.21  4917.2 1985.51  4960.0 1984.56
  4995.4 1979.63  5008.5 1979.12  5008.8 1978.62  5012.3 1978.62  5012.5 1979.12
  5049.4 1980.98  5055.1 1983.26  5071.7 1985.01  5211.0 1988.16  5252.3 1990.30
  5277.8 1990.76  5284.8 1991.86  5316.8 1992.66  5322.4 1992.19  5340.6 1993.08
#Mann=8,-1,0
  4548.4    0.16       0  4551.8    0.07       0  4673.3    0.16       0
  4673.6    0.07       0  4917.2    0.16       0  5008.5    0.07       0
  5012.5    0.16       0  5252.3    0.07       0
Bank Sta=5008.5,5012.5
Exp/Cntr=0.3,0.1

Type RM Length L Ch R = 1,10362,255,255,255
BEGIN DESCRIPTION:
Stink Creek Trib3 12.0
END DESCRIPTION:
XS GIS Cut Line= 3
      1438255.01      6864488.01      1438555.09      6864767.84
      1438855.00      6864588.00
#Sta/Elev= 30
  4589.7 1994.27  4639.3 1990.39  4702.8 1987.54  4724.3 1987.61  4762.7 1986.31
  4851.3 1985.29  4879.6 1984.27  4893.8 1984.92  4936.3 1983.68  4964.6 1984.05
  4978.8 1985.81  4986.1 1983.62  4993.0 1982.89  4996.5 1981.27  5016.1 1980.61
  5032.9 1980.30  5033.1 1979.80  5036.9 1980.30  5050.3 1980.80  5065.9 1982.52
  5071.7 1982.17  5081.4 1983.75  5093.2 1984.40  5116.5 1983.97  5139.8 1984.55
  5145.6 1985.37  5246.7 1986.91  5314.7 1991.02  5326.4 1992.60  5349.7 1993.55
#Mann=5,-1,0
  4589.7    0.16       0  4762.7    0.07       0  5016.1    0.16       0
  5032.9    0.07       0  5036.9    0.16       0
Bank Sta=5032.9,5036.9
Exp/Cntr=0.3,0.1

Type RM Length L Ch R = 1,10107,221,221,221
BEGIN DESCRIPTION:
Stink Creek Trib3 11.0
END DESCRIPTION:
XS GIS Cut Line= 3
      1438154.96      6864587.97      1438575.35      6864968.00
      1438951.04      6864845.04
#Sta/Elev= 30
  4433.3 1996.05  4461.4 1994.53  4516.2 1989.49  4647.5 1985.28  4656.2 1985.21
  4801.4 1983.33  4808.8 1982.38  4844.0 1982.78  4851.2 1983.79  4864.9 1982.97
  4871.5 1980.90  4929.1 1979.51  4934.9 1980.62  4943.3 1980.75  4950.1 1983.13
  4957.5 1983.54  4971.7 1982.73  4978.5 1980.82  4990.7 1979.20  4990.9 1978.70
  4994.7 1979.20  5010.2 1979.38  5031.2 1981.14  5047.6 1981.08  5079.5 1983.24
  5148.4 1983.04  5189.0 1985.34  5275.9 1987.15  5302.5 1989.05  5395.3 1991.07
#Mann=8,-1,0
  4433.3    0.07       0  4516.2    0.16       0  4647.5    0.07       0
  4656.2    0.16       0  4871.5    0.07       0  4934.9    0.16       0
  4990.7    0.07       0  4994.7    0.16       0
Bank Sta=4990.7,4994.7
Exp/Cntr=0.3,0.1

Type RM Length L Ch R = 1,9886,1003,1003,1003
BEGIN DESCRIPTION:
Stink Creek Trib3 4171
END DESCRIPTION:
XS GIS Cut Line= 3
      1437706.20      6865295.44      1438538.56      6865155.13
      1438911.35      6865007.38
#Sta/Elev= 30
  4155.9 1987.77  4195.2 1986.68  4225.7 1981.02  4256.1 1978.50  4276.4 1978.26
  4316.9 1981.15  4448.8 1978.69  4550.2 1979.25  4631.3 1977.03  4783.4 1978.56
  4830.7 1977.14  4835.8 1980.39  4882.8 1975.90  4883.1 1975.40  4886.8 1975.90
  4896.3 1977.44  4951.7 1977.31  4956.8 1976.33  5009.0 1976.47  5028.0 1977.76
  5033.4 1976.22  5057.7 1977.88  5063.1 1976.91  5093.0 1979.18  5111.7 1979.10
  5117.1 1980.63  5136.0 1980.70  5146.8 1983.21  5303.5 1991.43  5401.0 1992.98
#Mann=3,-1,0
  4155.9   0.035       0  4882.8   0.035       0  4886.8   0.035       0
Bank Sta=4882.8,4886.8
Exp/Cntr=0.3,0.1

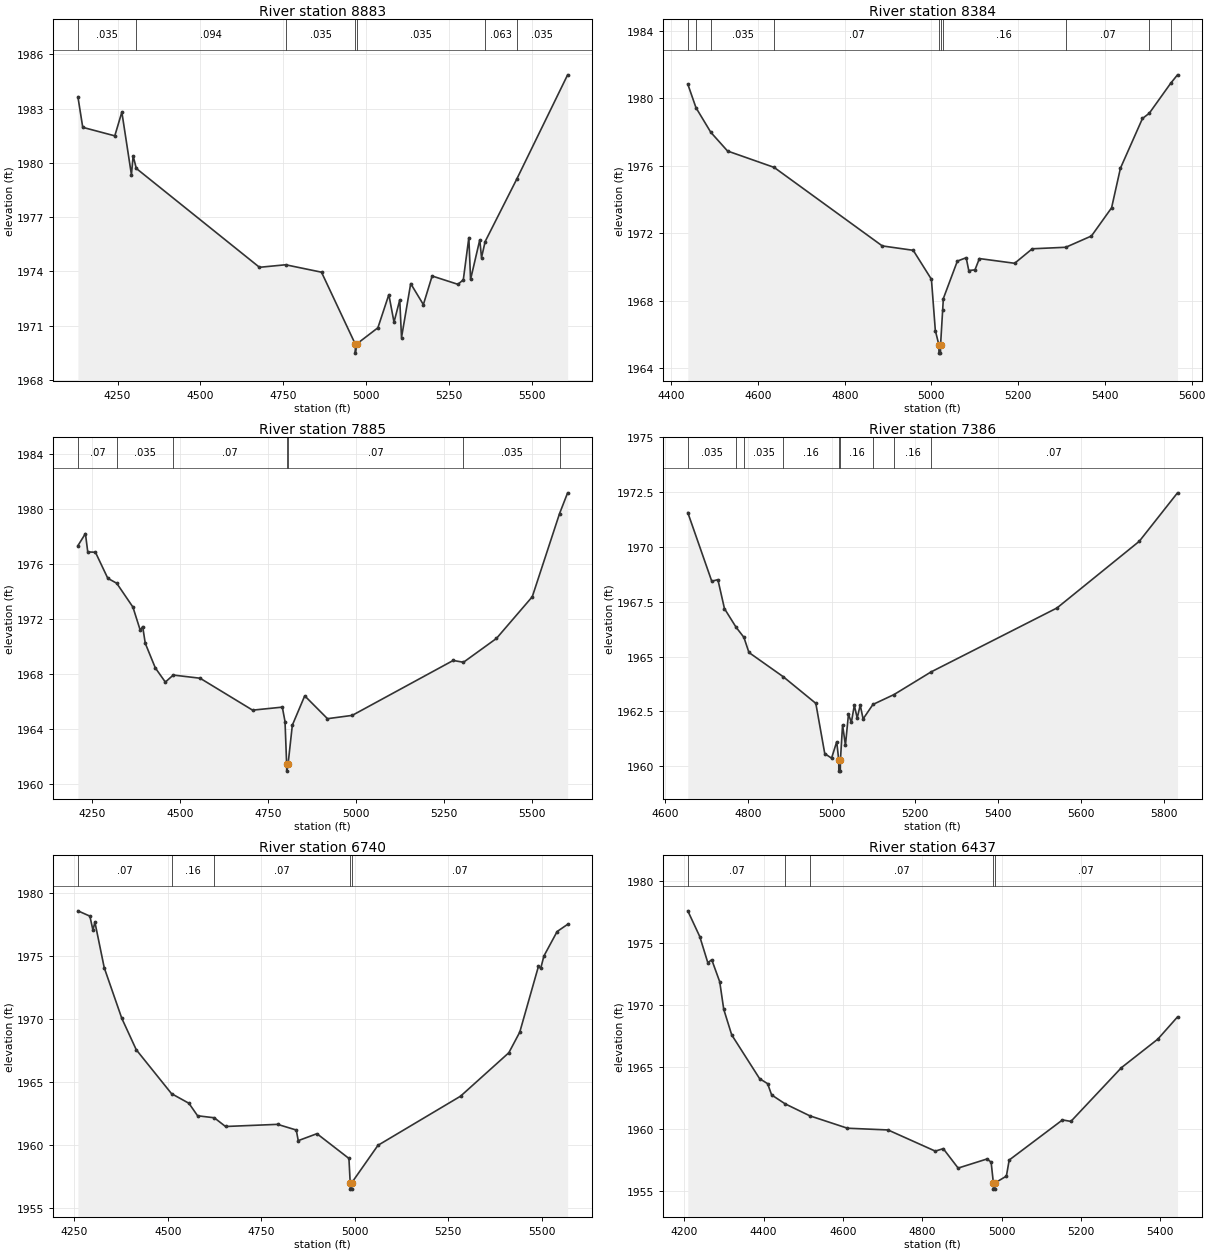
Type RM Length L Ch R = 1,8883,499,499,499
BEGIN DESCRIPTION:
Stink Creek Trib3 9.0
END DESCRIPTION:
XS GIS Cut Line= 3
      1437217.92      6865857.50      1438055.10      6865622.64
      1438636.11      6865447.26
#Sta/Elev= 30
  4130.5 1983.65  4145.1 1981.96  4241.7 1981.49  4263.0 1982.80  4291.9 1979.34
  4297.0 1980.38  4306.6 1979.69  4677.9 1974.23  4756.8 1974.37  4864.9 1973.96
  4966.7 1969.99  4967.0 1969.49  4970.7 1969.99  5034.9 1970.89  5067.9 1972.72
  5083.5 1971.20  5100.8 1972.43  5106.1 1970.35  5133.8 1973.33  5172.0 1972.17
  5198.4 1973.75  5276.1 1973.29  5292.4 1973.54  5309.1 1975.87  5314.3 1973.56
  5342.1 1975.75  5347.3 1974.76  5358.2 1975.65  5453.5 1979.10  5606.9 1984.86
#Mann=7,-1,0
  4130.5   0.035       0  4306.6   0.094       0  4756.8   0.035       0
  4966.7   0.035       0  4970.7   0.035       0  5358.2   0.063       0
  5453.5   0.035       0
Bank Sta=4966.7,4970.7
Exp/Cntr=0.3,0.1

Type RM Length L Ch R = 1,8384,499,499,499
BEGIN DESCRIPTION:
Stink Creek Trib3 8.0
END DESCRIPTION:
XS GIS Cut Line= 3
      1437304.98      6865889.84      1437856.18      6865998.48
      1438414.54      6865897.62
#Sta/Elev= 30
  4438.2 1980.85  4457.1 1979.45  4491.3 1977.99  4529.9 1976.88  4637.2 1975.91
  4886.7 1971.25  4958.0 1970.99  5000.0 1969.27  5009.0 1966.23  5017.1 1965.39
  5017.4 1964.89  5020.9 1964.89  5021.1 1965.39  5025.9 1967.45  5027.5 1968.13
  5059.8 1970.35  5080.1 1970.55  5086.1 1969.79  5100.4 1969.83  5110.6 1970.50
  5191.9 1970.22  5232.5 1971.08  5309.8 1971.17  5369.0 1971.84  5415.4 1973.51
  5435.8 1975.86  5486.6 1978.81  5502.3 1979.12  5551.7 1980.90  5567.4 1981.40
#Mann=10,-1,0
  4438.2   0.035       0  4457.1    0.07       0  4491.3   0.035       0
  4637.2    0.07       0  5017.1    0.07       0  5021.1    0.07       0
  5025.9    0.16       0  5309.8    0.07       0  5502.3   0.035       0
  5551.7    0.07       0
Bank Sta=5017.1,5021.1
Exp/Cntr=0.3,0.1

Type RM Length L Ch R = 1,7885,499,499,499
BEGIN DESCRIPTION:
Stink Creek Trib3 7.0
END DESCRIPTION:
XS GIS Cut Line= 3
      1437455.03      6866937.98      1438055.50      6866424.16
      1438555.01      6866087.99
#Sta/Elev= 30
  4209.7 1977.34  4231.1 1978.22  4237.7 1976.89  4259.6 1976.86  4294.7 1974.97
  4320.1 1974.61  4366.1 1972.88  4386.9 1971.20  4393.9 1971.46  4401.2 1970.25
  4429.8 1968.46  4458.3 1967.43  4480.8 1967.94  4557.1 1967.71  4706.4 1965.39
  4790.9 1965.61  4798.6 1964.56  4803.2 1961.46  4803.4 1960.96  4807.2 1961.46
  4819.4 1964.30  4854.6 1966.43  4919.3 1964.77  4989.6 1965.01  5276.7 1969.00
  5306.0 1968.87  5399.7 1970.60  5501.6 1973.63  5579.1 1979.67  5602.1 1981.18
#Mann=7,-1,0
  4209.7    0.07       0  4320.1   0.035       0  4480.8    0.07       0
  4803.2    0.07       0  4807.2    0.07       0  5306.0   0.035       0
  5579.1    0.07       0
Bank Sta=4803.2,4807.2
Exp/Cntr=0.3,0.1

Type RM Length L Ch R = 1,7386,646,646,646
BEGIN DESCRIPTION:
Stink Creek Trib3 6.0
END DESCRIPTION:
XS GIS Cut Line= 3
      1437655.02      6867037.99      1437954.95      6866865.27
      1438555.04      6866287.97
#Sta/Elev= 30
  4653.9 1971.57  4711.6 1968.44  4726.4 1968.51  4742.2 1967.19  4770.2 1966.34
  4789.0 1965.88  4801.1 1965.19  4884.0 1964.08  4962.1 1962.87  4983.6 1960.58
  5000.0 1960.37  5012.4 1961.12  5017.3 1960.28  5017.5 1959.78  5021.0 1959.78
  5021.3 1960.28  5026.5 1961.89  5033.4 1960.96  5040.7 1962.38  5047.6 1962.00
  5054.8 1962.78  5061.7 1962.20  5069.0 1962.79  5075.9 1962.16  5099.6 1962.82
  5150.2 1963.27  5239.2 1964.30  5542.6 1967.22  5740.7 1970.26  5832.7 1972.47
#Mann=9,-1,0
  4653.9   0.035       0  4770.2    0.16       0  4789.0   0.035       0
  4884.0    0.16       0  5017.3    0.07       0  5021.3    0.16       0
  5099.6    0.07       0  5150.2    0.16       0  5239.2    0.07       0
Bank Sta=5017.3,5021.3
Exp/Cntr=0.3,0.1

Type RM Length L Ch R = 1,6740,303,303,303
BEGIN DESCRIPTION:
Stink Creek Trib3 5.0
END DESCRIPTION:
XS GIS Cut Line= 3
      1437654.97      6867438.01      1438348.98      6867179.19
      1438804.98      6866838.02
#Sta/Elev= 30
  4259.3 1978.55  4291.3 1978.13  4299.5 1977.03  4304.8 1977.65  4329.8 1974.04
  4376.7 1970.04  4415.4 1967.55  4509.8 1964.07  4556.3 1963.31  4579.5 1962.32
  4624.2 1962.16  4654.2 1961.47  4793.5 1961.64  4843.5 1961.19  4848.8 1960.35
  4898.8 1960.90  4984.4 1958.94  4987.8 1957.01  4988.0 1956.51  4991.5 1956.51
  4991.8 1957.01  5062.1 1959.98  5283.0 1963.87  5412.2 1967.31  5441.4 1968.94
  5491.4 1974.15  5497.6 1974.00  5506.0 1974.97  5541.4 1976.91  5569.5 1977.48
#Mann=5,-1,0
  4259.3    0.07       0  4509.8    0.16       0  4624.2    0.07       0
  4987.8    0.07       0  4991.8    0.07       0
Bank Sta=4987.8,4991.8
Exp/Cntr=0.3,0.1

Type RM Length L Ch R = 1,6437,498,498,498
BEGIN DESCRIPTION:
Stink Creek Trib3 4.0
END DESCRIPTION:
XS GIS Cut Line= 3
      1437704.99      6867488.00      1438491.12      6867401.24
      1438804.97      6867088.03
#Sta/Elev= 30
  4209.1 1977.63  4239.3 1975.55  4259.6 1973.44  4269.5 1973.68  4289.6 1971.90
  4299.7 1969.68  4319.8 1967.61  4390.2 1964.07  4410.3 1963.67  4420.4 1962.76
  4454.4 1962.04  4516.8 1961.07  4611.5 1960.07  4713.8 1959.93  4832.9 1958.22
  4853.0 1958.42  4890.5 1956.85  4963.7 1957.59  4973.7 1957.32  4979.3 1955.65
  4979.6 1955.15  4983.1 1955.15  4983.3 1955.65  5012.1 1956.20  5019.2 1957.50
  5153.5 1960.74  5174.7 1960.62  5302.0 1964.96  5393.9 1967.27  5443.4 1969.06
#Mann=5,-1,0
  4209.1    0.07       0  4454.4    0.16       0  4516.8    0.07       0
  4979.3    0.07       0  4983.3    0.07       0
Bank Sta=4979.3,4983.3
Exp/Cntr=0.3,0.1

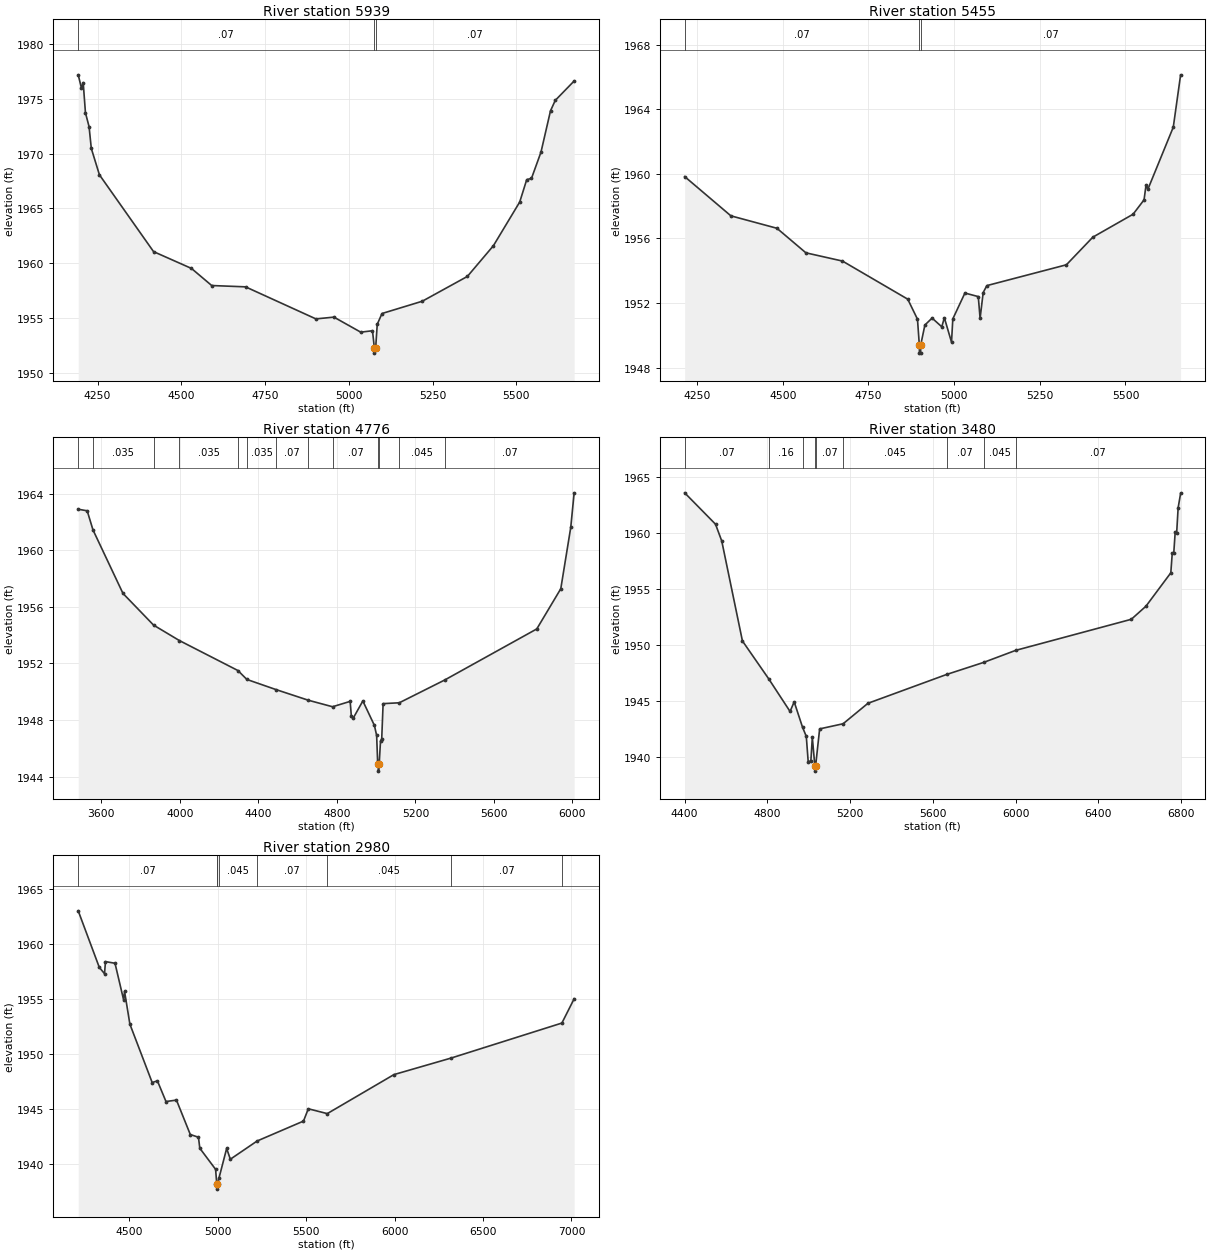
Type RM Length L Ch R = 1,5939,484,484,484
BEGIN DESCRIPTION:
Stink Creek Trib3 3.0
END DESCRIPTION:
XS GIS Cut Line= 3
      1437754.96      6867537.98      1438505.07      6867838.03
      1439004.96      6867388.03
#Sta/Elev= 30
  4192.1 1977.17  4201.6 1975.98  4207.0 1976.46  4213.7 1973.71  4224.5 1972.45
  4231.2 1970.46  4255.4 1968.06  4417.0 1961.06  4530.1 1959.53  4590.6 1957.97
  4691.6 1957.85  4901.6 1954.93  4955.5 1955.09  5035.5 1953.72  5070.6 1953.85
  5076.1 1952.31  5076.3 1951.81  5080.1 1952.31  5084.8 1954.44  5099.0 1955.42
  5219.3 1956.54  5353.9 1958.80  5431.6 1961.60  5510.1 1965.58  5531.0 1967.62
  5545.2 1967.73  5573.6 1970.13  5602.0 1973.89  5616.2 1974.84  5672.6 1976.61
#Mann=3,-1,0
  4192.1    0.07       0  5076.1    0.07       0  5080.1    0.07       0
Bank Sta=5076.1,5080.1
Exp/Cntr=0.3,0.1

Type RM Length L Ch R = 1,5455,679,679,679
BEGIN DESCRIPTION:
Stink Creek Trib3 2.0
END DESCRIPTION:
XS GIS Cut Line= 3
      1438004.99      6867737.99      1438585.40      6868268.16
      1439205.03      6868037.99
#Sta/Elev= 30
  4213.9 1959.83  4348.7 1957.40  4483.1 1956.63  4567.6 1955.11  4674.3 1954.60
  4864.8 1952.24  4893.2 1951.00  4898.6 1949.40  4898.9 1948.90  4902.4 1948.90
  4902.6 1949.40  4914.8 1950.64  4935.8 1951.07  4964.1 1950.53  4971.6 1951.09
  4992.5 1949.58  4996.3 1951.02  5031.6 1952.62  5070.6 1952.40  5075.9 1951.05
  5084.9 1952.65  5095.6 1953.08  5327.8 1954.37  5404.9 1956.08  5522.3 1957.50
  5554.3 1958.39  5560.0 1959.29  5565.4 1959.04  5639.6 1962.89  5661.0 1966.13
#Mann=3,-1,0
  4213.9    0.07       0  4898.6    0.07       0  4902.6    0.07       0
Bank Sta=4898.6,4902.6
Exp/Cntr=0.3,0.1

Type RM Length L Ch R = 1,4776,1296,1296,1296
BEGIN DESCRIPTION:
Stink Creek Trib3 1.1
END DESCRIPTION:
XS GIS Cut Line= 3
      1437071.80      6868049.39      1438385.90      6868808.51
      1439213.91      6868232.78
#Sta/Elev= 30
  3482.4 1962.89  3528.1 1962.78  3557.6 1961.43  3710.4 1956.94  3866.3 1954.70
  3997.6 1953.61  4295.9 1951.49  4341.5 1950.86  4490.6 1950.14  4654.7 1949.39
  4777.9 1948.93  4867.6 1949.31  4873.4 1948.30  4883.4 1948.13  4932.2 1949.34
  4991.1 1947.61  5002.5 1946.90  5007.3 1945.11  5011.4 1944.88  5011.7 1944.38
  5015.4 1944.88  5022.2 1946.51  5028.3 1946.65  5035.4 1949.15  5117.7 1949.21
  5349.1 1950.82  5818.2 1954.43  5940.4 1957.27  5991.1 1961.60  6008.5 1964.05
#Mann=13,-1,0
  3482.4    0.07       0  3557.6   0.035       0  3866.3    0.07       0
  3997.6   0.035       0  4295.9    0.07       0  4341.5   0.035       0
  4490.6    0.07       0  4654.7   0.035       0  4777.9    0.07       0
  5011.4    0.07       0  5015.4    0.07       0  5117.7   0.045       0
  5349.1    0.07       0
Bank Sta=5011.4,5015.4
Exp/Cntr=0.3,0.1

Type RM Length L Ch R = 1,3480,500,500,500
BEGIN DESCRIPTION:
Stink Creek Trib3 1.0
END DESCRIPTION:
XS GIS Cut Line= 3
      1437405.93      6869633.48      1438005.23      6869622.86
      1439281.20      6868357.22
#Sta/Elev= 30
  4400.6 1963.61  4549.7 1960.80  4579.7 1959.30  4679.7 1950.35  4806.7 1946.96
  4909.8 1944.04  4929.8 1944.90  4970.1 1942.63  4988.3 1941.81  4997.4 1939.56
  5010.4 1939.61  5017.4 1941.72  5029.5 1939.20  5029.8 1938.70  5033.5 1939.20
  5052.8 1942.48  5166.2 1942.94  5286.1 1944.77  5666.1 1947.35  5845.1 1948.43
  6000.4 1949.51  6558.9 1952.29  6629.6 1953.46  6749.8 1956.45  6756.9 1958.24
  6764.0 1958.19  6771.1 1960.13  6778.1 1960.02  6785.2 1962.27  6797.2 1963.56
#Mann=9,-1,0
  4400.6    0.07       0  4806.7    0.16       0  4970.1    0.07       0
  5029.5    0.07       0  5033.5    0.07       0  5166.2   0.045       0
  5666.1    0.07       0  5845.1   0.045       0  6000.4    0.07       0
Bank Sta=5029.5,5033.5
Exp/Cntr=0.3,0.1

Type RM Length L Ch R = 1,2980,0,0,0
BEGIN DESCRIPTION:
Stink Creek Trib3 1840
END DESCRIPTION:
XS GIS Cut Line= 3
      1437423.74      6869777.07      1438155.67      6870069.54
      1439405.02      6868487.97
#Sta/Elev= 30
  4211.8 1963.04  4330.9 1957.90  4360.5 1957.32  4365.9 1958.42  4419.8 1958.27
  4468.3 1954.95  4473.7 1955.72  4503.9 1952.73  4629.9 1947.42  4659.5 1947.57
  4708.0 1945.69  4767.3 1945.82  4845.4 1942.69  4891.6 1942.44  4899.2 1941.44
  4988.5 1939.52  4994.9 1938.22  4995.2 1937.72  4999.0 1938.22  5008.3 1938.77
  5051.0 1941.42  5071.8 1940.44  5223.4 1942.10  5485.4 1943.91  5512.6 1945.03
  5619.8 1944.59  5996.7 1948.14  6318.9 1949.64  6946.2 1952.83  7015.5 1955.04
#Mann=8,-1,0
  4211.8    0.07       0  4994.9    0.07       0  4999.0    0.07       0
  5008.3   0.045       0  5223.4    0.07       0  5619.8   0.045       0
  6318.9    0.07       0  6946.2   0.035       0
Bank Sta=4994.9,4999
Exp/Cntr=0.3,0.1

Chan Stop Cuts=-1