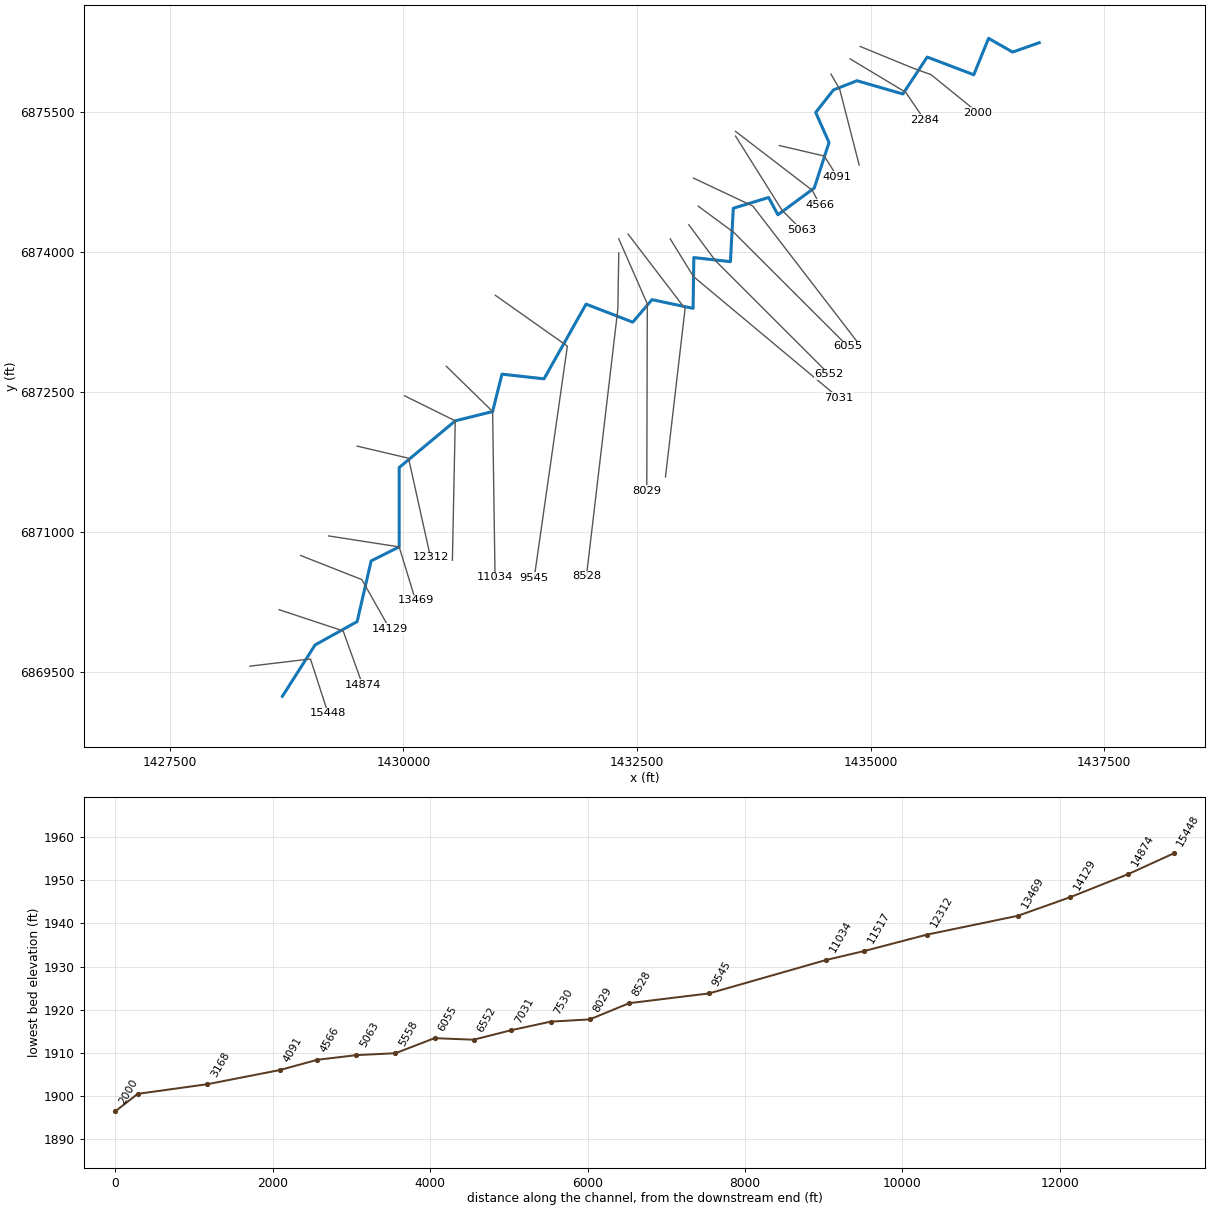
--- Stink Creek Trib4.prj (project) ---

Proj Title=Stink Creek Trib4 Base Level Engineering
Current Plan=p01
Default Exp/Contr=0.3,0.1
English Units
Geom File=g01
Flow File=f01
Plan File=p01
BEGIN DESCRIPTION:
Stink Creek Trib4
END DESCRIPTION:

--- Stink Creek Trib4.p01 (plan) ---

Plan Title=Multiple Run
Short Identifier=Multiple
Geom File=g01
Flow File=f01
Subcritical Flow
K Sum by GR= 0
Std Step Tol= 0.01
Critical Tol= 0.01
Num of Std Step Trials= 20
Max Error Tol= 0.3
Flow Tol Ratio= 0.001
Split Flow NTrial= 30
Split Flow Tol= 0.02
Split Flow Ratio= 0.02
Log Output Level= 0
Friction Slope Method= 1
Unsteady Friction Slope Method= 2
Unsteady Bridges Friction Slope Method= 1
Parabolic Critical Depth
Global Vel Dist=  1 , 1 , 1
Global Log Level= 0
CheckData=True
Encroach Param= -1, 0, 0, 0
BEGIN DESCRIPTION:
Multiple Run
END DESCRIPTION:

--- Stink Creek Trib4.f01 (steady flow) ---

Flow Title=Multiple
Number of Profiles=7
Profile Names=10-year,25-year,50-year,1pct_min,100-year,1pct_plu,500-year
River Rch & RM= Stink Creek Trib,Reach-1,15448
     210     292     360     221     441     880     670
River Rch & RM= Stink Creek Trib,Reach-1,13469
     382     547     686     428     854    1703    1338
River Rch & RM= Stink Creek Trib,Reach-1,8029
     422     603     757     471     940    1876    1471
Boundary for River Rch & Prof#=Stink Creek Trib,Reach-1,1
Up Type=0
Dn Type=3
Dn Slope=0.005
Boundary for River Rch & Prof#=Stink Creek Trib,Reach-1,2
Up Type=0
Dn Type=3
Dn Slope=0.005
Boundary for River Rch & Prof#=Stink Creek Trib,Reach-1,3
Up Type=0
Dn Type=3
Dn Slope=0.005
Boundary for River Rch & Prof#=Stink Creek Trib,Reach-1,4
Up Type=0
Dn Type=3
Dn Slope=0.005
Boundary for River Rch & Prof#=Stink Creek Trib,Reach-1,5
Up Type=0
Dn Type=3
Dn Slope=0.005
Boundary for River Rch & Prof#=Stink Creek Trib,Reach-1,6
Up Type=0
Dn Type=3
Dn Slope=0.005
Boundary for River Rch & Prof#=Stink Creek Trib,Reach-1,7
Up Type=0
Dn Type=3
Dn Slope=0.005

--- Stink Creek Trib4.g01 (geometry) ---

Geom Title=Existing Conditions

River Reach=Stink Creek Trib,Reach-1
Reach XY= 30
      1428705.00      6869238.00      1429055.00      6869788.00
      1429505.00      6870038.00      1429655.00      6870688.00
      1429955.00      6870838.00      1429955.00      6871688.00
      1430555.00      6872188.00      1430955.00      6872288.00
      1431055.00      6872688.00      1431505.00      6872638.00
      1431955.00      6873438.00      1432454.91      6873245.28
      1432660.69      6873486.12      1433100.41      6873393.11
      1433108.53      6873937.01      1433500.00      6873892.99
      1433530.97      6874465.35      1433908.69      6874580.35
      1434008.41      6874395.38      1434397.52      6874681.94
      1434555.39      6875169.66      1434412.83      6875491.23
      1434602.57      6875732.48      1434855.30      6875830.80
      1435345.54      6875689.02      1435606.26      6876084.52
      1436104.80      6875894.98      1436262.65      6876285.03
      1436520.34      6876137.95      1436805.00      6876238.00

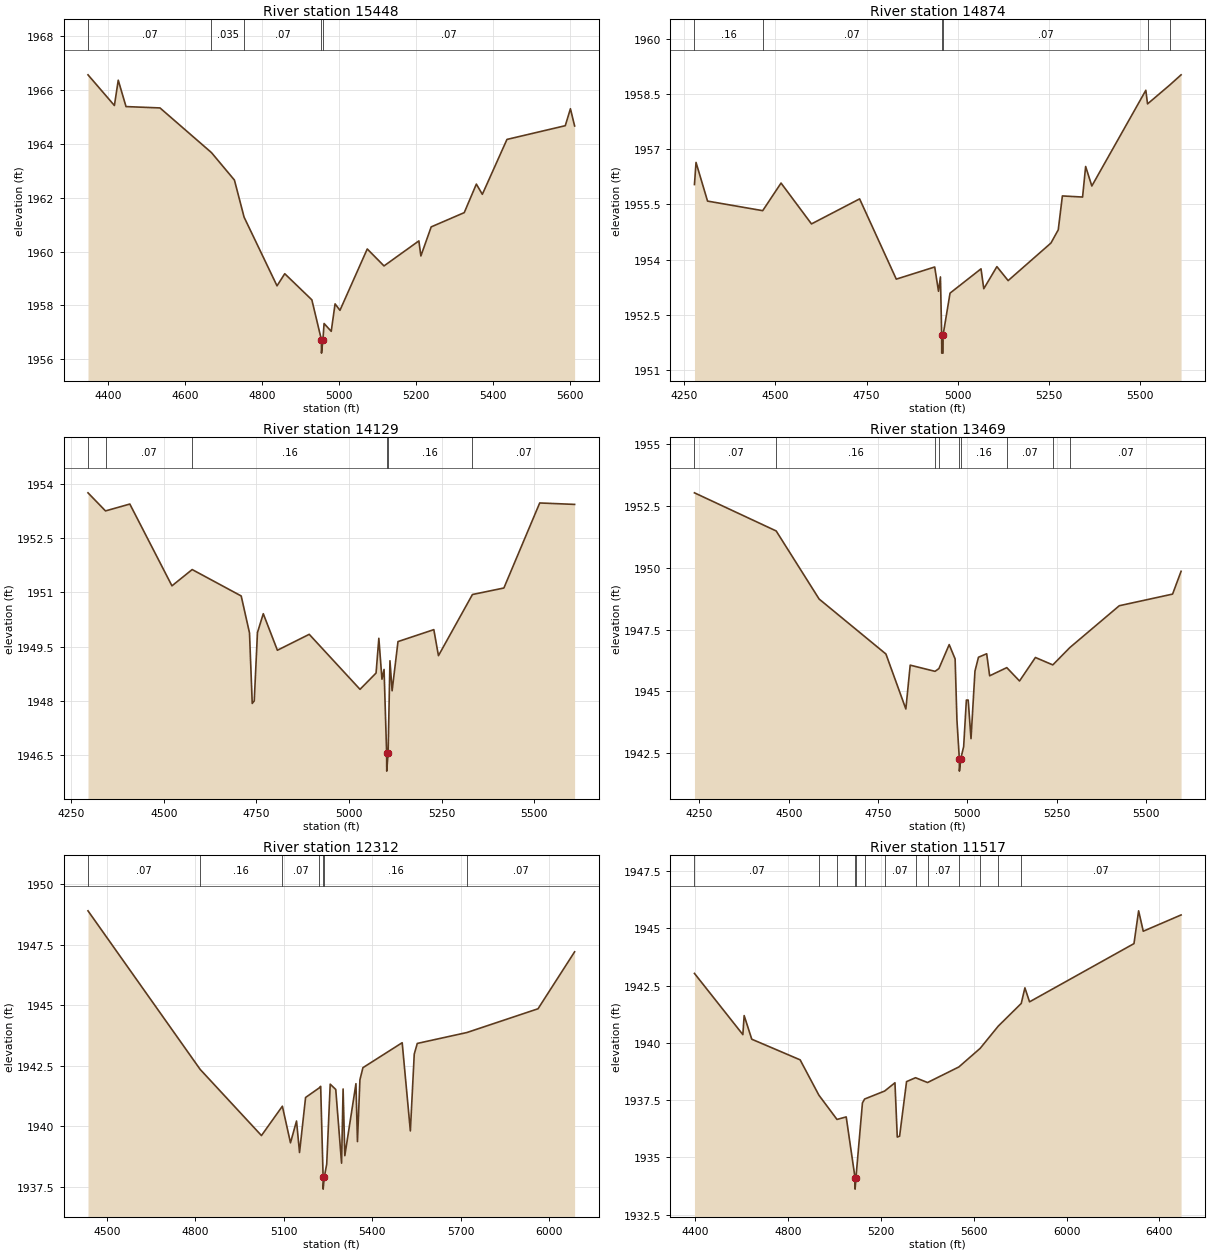
Type RM Length L Ch R = 1,15448,574,574,574
BEGIN DESCRIPTION:
Stink Creek Trib4 17.0
END DESCRIPTION:
XS GIS Cut Line= 3
      1428356.83      6869560.40      1429005.00      6869638.00
      1429194.06      6869054.88
#Sta/Elev= 30
  4347.2 1966.57  4415.9 1965.43  4425.9 1966.37  4446.1 1965.39  4534.5 1965.34
  4668.4 1963.68  4728.1 1962.66  4753.3 1961.28  4838.9 1958.73  4859.0 1959.18
  4929.5 1958.21  4954.3 1956.73  4954.6 1956.23  4958.3 1956.73  4961.3 1957.33
  4979.9 1957.04  4989.9 1958.06  5002.6 1957.82  5073.6 1960.10  5117.2 1959.47
  5207.9 1960.40  5213.1 1959.84  5239.9 1960.92  5325.9 1961.45  5357.4 1962.51
  5373.0 1962.13  5437.0 1964.17  5588.7 1964.68  5602.1 1965.31  5613.0 1964.67
#Mann=5,-1,0
  4347.2    0.07       0  4668.4   0.035       0  4753.3    0.07       0
  4954.3    0.07       0  4958.3    0.07       0
Bank Sta=4954.3,4958.3
Exp/Cntr=0.3,0.1

Type RM Length L Ch R = 1,14874,745,745,745
BEGIN DESCRIPTION:
Stink Creek Trib4 16.0
END DESCRIPTION:
XS GIS Cut Line= 3
      1428669.59      6870165.55      1429355.00      6869938.00
      1429562.61      6869361.65
#Sta/Elev= 30
  4277.8 1956.04  4282.1 1956.64  4313.7 1955.59  4465.0 1955.33  4515.3 1956.08
  4598.8 1954.97  4730.8 1955.65  4831.4 1953.47  4936.8 1953.80  4947.2 1953.14
  4952.5 1953.53  4955.9 1951.96  4956.1 1951.46  4959.6 1951.46  4959.9 1951.96
  4978.9 1953.09  5063.8 1953.75  5071.4 1953.21  5107.4 1953.81  5138.2 1953.43
  5255.6 1954.45  5275.7 1954.81  5287.0 1955.73  5342.4 1955.70  5350.8 1956.53
  5367.8 1956.00  5515.9 1958.60  5520.6 1958.23  5581.2 1958.74  5612.6 1959.02
#Mann=6,-1,0
  4277.8    0.16       0  4465.0    0.07       0  4955.9    0.07       0
  4959.9    0.07       0  5520.6    0.16       0  5581.2    0.07       0
Bank Sta=4955.9,4959.9
Exp/Cntr=0.3,0.1

Type RM Length L Ch R = 1,14129,660,660,660
BEGIN DESCRIPTION:
Stink Creek Trib4 15.0
END DESCRIPTION:
XS GIS Cut Line= 3
      1428899.38      6870746.11      1429555.00      6870488.00
      1429854.75      6869958.10
#Sta/Elev= 30
  4295.4 1953.75  4342.7 1953.25  4408.3 1953.44  4522.0 1951.18  4576.6 1951.63
  4708.9 1950.90  4731.3 1949.88  4738.7 1947.93  4744.1 1948.00  4752.8 1949.89
  4768.5 1950.41  4806.6 1949.40  4892.5 1949.84  5029.6 1948.32  5072.9 1948.77
  5080.4 1949.73  5088.8 1948.60  5094.5 1948.87  5101.4 1946.56  5101.7 1946.06
  5105.4 1946.56  5110.4 1949.11  5116.2 1948.28  5132.1 1949.64  5228.8 1949.97
  5241.3 1949.25  5333.0 1950.94  5417.9 1951.12  5514.6 1953.47  5608.8 1953.43
#Mann=6,-1,0
  4295.4    0.16       0  4342.7    0.07       0  4576.6    0.16       0
  5101.4    0.07       0  5105.4    0.16       0  5333.0    0.07       0
Bank Sta=5101.4,5105.4
Exp/Cntr=0.3,0.1

Type RM Length L Ch R = 1,13469,1157,1157,1157
BEGIN DESCRIPTION:
Stink Creek Trib4 14.0
END DESCRIPTION:
XS GIS Cut Line= 3
      1429199.97      6870955.39      1429955.00      6870838.00
      1430129.85      6870265.19
#Sta/Elev= 30
  4235.9 1953.02  4464.8 1951.48  4585.1 1948.73  4772.2 1946.51  4828.0 1944.29
  4840.2 1946.06  4909.7 1945.81  4920.5 1945.92  4949.4 1946.89  4966.0 1946.31
  4971.1 1943.84  4977.8 1942.28  4978.0 1941.78  4981.8 1942.28  4989.9 1942.77
  4997.5 1944.65  5002.6 1944.65  5010.5 1943.09  5021.6 1945.82  5031.4 1946.38
  5054.4 1946.52  5062.7 1945.63  5110.7 1945.96  5146.4 1945.42  5190.9 1946.37
  5239.6 1946.07  5287.3 1946.77  5425.8 1948.46  5575.1 1948.93  5598.9 1949.85
#Mann=9,-1,0
  4235.9    0.07       0  4464.8    0.16       0  4909.7    0.07       0
  4920.5    0.16       0  4977.8    0.07       0  4981.8    0.16       0
  5110.7    0.07       0  5239.6    0.16       0  5287.3    0.07       0
Bank Sta=4977.8,4981.8
Exp/Cntr=0.3,0.1

Type RM Length L Ch R = 1,12312,795,795,795
BEGIN DESCRIPTION:
Stink Creek Trib4 13.0
END DESCRIPTION:
XS GIS Cut Line= 3
      1429505.87      6871917.08      1430055.00      6871788.00
      1430290.06      6870726.82
#Sta/Elev= 30
  4435.9 1948.89  4816.4 1942.35  5024.4 1939.62  5095.4 1940.83  5122.9 1939.32
  5143.4 1940.22  5153.6 1938.92  5174.1 1941.19  5220.9 1941.59  5225.3 1941.65
  5233.6 1937.91  5233.8 1937.41  5237.6 1937.91  5245.8 1938.44  5257.7 1941.74
  5276.5 1941.52  5296.2 1938.48  5301.4 1941.54  5307.3 1938.79  5345.0 1941.76
  5350.1 1939.37  5358.5 1941.92  5368.7 1942.42  5501.9 1943.45  5529.6 1939.81
  5542.8 1942.98  5553.1 1943.42  5721.5 1943.87  5962.8 1944.85  6086.9 1947.20
#Mann=7,-1,0
  4435.9    0.07       0  4816.4    0.16       0  5095.4    0.07       0
  5220.9    0.16       0  5233.6    0.07       0  5237.6    0.16       0
  5721.5    0.07       0
Bank Sta=5233.6,5237.6
Exp/Cntr=0.3,0.1

Type RM Length L Ch R = 1,11517,483,483,483
BEGIN DESCRIPTION:
Stink Creek Trib4 12.0
END DESCRIPTION:
XS GIS Cut Line= 3
      1430013.63      6872455.82      1430555.00      6872188.00
      1430524.35      6870695.01
#Sta/Elev= 30
  4396.0 1943.03  4604.6 1940.36  4610.2 1941.19  4643.0 1940.16  4851.4 1939.26
  4932.2 1937.72  5010.3 1936.66  5050.0 1936.77  5088.0 1934.12  5088.3 1933.62
  5092.0 1934.12  5120.0 1937.38  5129.3 1937.55  5215.9 1937.90  5260.1 1938.26
  5270.1 1935.89  5280.1 1935.93  5310.1 1938.31  5348.8 1938.48  5400.6 1938.27
  5535.6 1938.95  5627.3 1939.76  5705.3 1940.73  5804.4 1941.72  5820.2 1942.40
  5840.2 1941.79  6290.3 1944.33  6310.3 1945.76  6330.3 1944.87  6493.3 1945.58
#Mann=13,-1,0
  4396.0    0.07       0  4932.2    0.16       0  5010.3    0.07       0
  5088.0    0.07       0  5092.0    0.07       0  5129.3    0.16       0
  5215.9    0.07       0  5348.8    0.16       0  5400.6    0.07       0
  5535.6    0.16       0  5627.3    0.07       0  5705.3    0.16       0
  5804.4    0.07       0
Bank Sta=5088,5092
Exp/Cntr=0.3,0.1

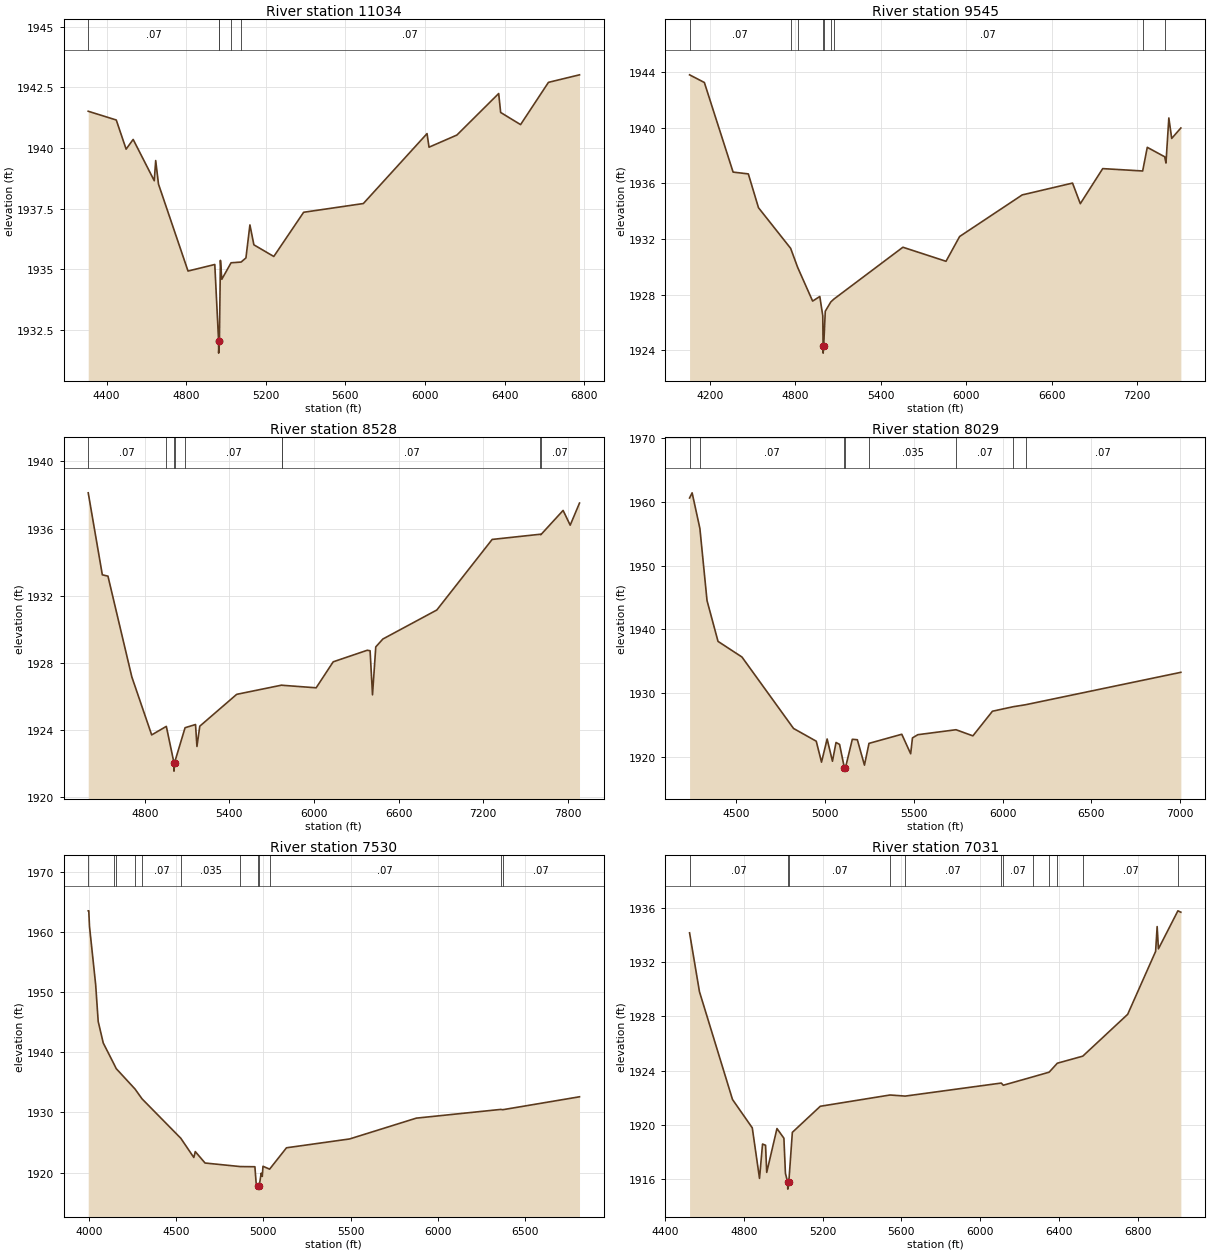
Type RM Length L Ch R = 1,11034,1489,1489,1489
BEGIN DESCRIPTION:
Stink Creek Trib4 11.0
END DESCRIPTION:
XS GIS Cut Line= 3
      1430459.80      6872772.08      1430955.00      6872288.00
      1430980.90      6870511.89
#Sta/Elev= 30
  4307.5 1941.51  4448.4 1941.15  4497.9 1939.95  4533.3 1940.35  4639.3 1938.65
  4646.5 1939.48  4660.6 1938.51  4809.0 1934.93  4943.5 1935.20  4962.6 1932.05
  4962.9 1931.55  4966.6 1932.05  4971.8 1935.37  4978.8 1934.59  5025.2 1935.27
  5075.7 1935.30  5100.0 1935.47  5120.0 1936.83  5140.0 1936.01  5240.0 1935.53
  5390.0 1937.35  5690.1 1937.71  6010.1 1940.59  6020.1 1940.03  6160.1 1940.53
  6370.1 1942.24  6380.1 1941.46  6480.2 1940.96  6620.2 1942.70  6776.3 1943.01
#Mann=5,-1,0
  4307.5    0.07       0  4962.6    0.07       0  4966.6    0.07       0
  5025.2    0.16       0  5075.7    0.07       0
Bank Sta=4962.6,4966.6
Exp/Cntr=0.3,0.1

Type RM Length L Ch R = 1,9545,1017,1017,1017
BEGIN DESCRIPTION:
Stink Creek Trib4 10.0
END DESCRIPTION:
XS GIS Cut Line= 3
      1430984.53      6873532.58      1431755.00      6872988.00
      1431399.92      6870504.46
#Sta/Elev= 30
  4056.5 1943.80  4160.4 1943.25  4362.4 1936.81  4469.4 1936.68  4540.8 1934.25
  4766.8 1931.33  4816.6 1929.95  4921.2 1927.54  4971.7 1927.87  4992.6 1926.48
  4994.9 1924.30  4995.2 1923.80  4998.9 1924.30  5010.1 1926.81  5049.1 1927.48
  5070.2 1927.68  5555.6 1931.41  5858.6 1930.40  5954.2 1932.18  6394.0 1935.17
  6747.6 1936.02  6802.4 1934.54  6959.7 1937.06  7240.5 1936.89  7272.9 1938.59
  7395.3 1937.91  7404.2 1937.46  7424.4 1940.70  7444.6 1939.23  7508.8 1939.98
#Mann=9,-1,0
  4056.5    0.07       0  4766.8    0.16       0  4816.6    0.07       0
  4994.9    0.07       0  4998.9    0.07       0  5049.1    0.16       0
  5070.2    0.07       0  7240.5    0.16       0  7395.3    0.07       0
Bank Sta=4994.9,4998.9
Exp/Cntr=0.3,0.1

Type RM Length L Ch R = 1,8528,499,499,499
BEGIN DESCRIPTION:
Stink Creek Trib4 9.0
END DESCRIPTION:
XS GIS Cut Line= 3
      1432305.00      6873988.02      1432295.41      6873386.80
      1431958.89      6870522.50
#Sta/Elev= 30
  4398.7 1938.13  4498.7 1933.24  4538.7 1933.16  4708.0 1927.15  4848.8 1923.69
  4952.8 1924.20  5006.9 1922.03  5007.1 1921.53  5010.9 1922.03  5085.8 1924.12
  5159.9 1924.31  5170.0 1923.00  5190.1 1924.21  5451.9 1926.11  5771.5 1926.66
  5776.2 1926.65  6015.7 1926.50  6136.6 1928.05  6378.2 1928.74  6398.3 1928.71
  6415.5 1926.08  6438.6 1928.94  6489.0 1929.41  6871.6 1931.14  7264.3 1935.35
  7606.4 1935.66  7609.6 1935.63  7767.7 1937.08  7818.0 1936.20  7884.0 1937.52
#Mann=9,-1,0
  4398.7    0.07       0  4952.8   0.035       0  5006.9   0.035       0
  5010.9   0.035       0  5085.8    0.07       0  5771.5   0.035       0
  5776.2    0.07       0  7606.4    0.16       0  7609.6    0.07       0
Bank Sta=5006.9,5010.9
Exp/Cntr=0.3,0.1

Type RM Length L Ch R = 1,8029,499,499,499
BEGIN DESCRIPTION:
Stink Creek Trib4 8.0
END DESCRIPTION:
XS GIS Cut Line= 3
      1432305.01      6874137.97      1432610.41      6873440.71
      1432605.00      6871438.02
#Sta/Elev= 30
  4238.8 1960.60  4253.2 1961.41  4296.9 1955.82  4337.0 1944.52  4398.9 1938.12
  4533.5 1935.67  4823.7 1924.47  4951.5 1922.47  4981.1 1919.19  5012.7 1922.82
  5042.7 1919.33  5062.7 1922.27  5082.7 1921.97  5109.9 1918.28  5110.4 1917.78
  5115.6 1918.28  5154.4 1922.77  5182.7 1922.70  5222.7 1918.72  5248.2 1922.13
  5432.7 1923.56  5482.7 1920.50  5492.7 1922.99  5522.7 1923.49  5737.8 1924.27
  5832.7 1923.31  5942.7 1927.17  6060.2 1927.88  6129.5 1928.19  7002.7 1933.27
#Mann=8,-1,0
  4238.8   0.035       0  4296.9    0.07       0  5109.9    0.07       0
  5115.6    0.07       0  5248.2   0.035       0  5737.8    0.07       0
  6060.2   0.035       0  6129.5    0.07       0
Bank Sta=5109.9,5115.6
Exp/Cntr=0.3,0.1

Type RM Length L Ch R = 1,7530,499,499,499
BEGIN DESCRIPTION:
Stink Creek Trib4 7.0
END DESCRIPTION:
XS GIS Cut Line= 3
      1432404.99      6874188.01      1433014.77      6873389.39
      1432805.00      6871587.96
#Sta/Elev= 30
  3995.2 1963.51  3998.4 1963.51  4002.5 1960.91  4037.8 1951.26  4052.4 1945.12
  4081.4 1941.54  4143.1 1938.03  4155.8 1937.28  4263.7 1933.89  4303.5 1932.27
  4526.4 1925.70  4601.0 1922.51  4609.3 1923.49  4665.5 1921.59  4866.9 1921.00
  4951.4 1920.97  4958.5 1918.24  4970.1 1917.75  4970.6 1917.25  4975.8 1917.75
  4987.5 1919.90  4993.8 1919.37  4997.7 1921.05  5035.8 1920.57  5132.5 1924.12
  5494.7 1925.59  5877.3 1929.05  6361.8 1930.50  6373.4 1930.45  6813.6 1932.60
#Mann=12,-1,0
  3995.2    0.07       0  4143.1   0.035       0  4155.8    0.07       0
  4263.7   0.035       0  4303.5    0.07       0  4526.4   0.035       0
  4866.9    0.16       0  4970.1    0.07       0  4975.8    0.16       0
  5035.8    0.07       0  6361.8   0.035       0  6373.4    0.07       0
Bank Sta=4970.1,4975.8
Exp/Cntr=0.3,0.1

Type RM Length L Ch R = 1,7031,479,479,479
BEGIN DESCRIPTION:
Stink Creek Trib4 6.0
END DESCRIPTION:
XS GIS Cut Line= 3
      1432855.02      6874137.97      1433105.10      6873732.96
      1434655.01      6872437.99
#Sta/Elev= 30
  4524.0 1934.15  4574.2 1929.82  4742.1 1921.88  4842.6 1919.79  4879.3 1916.07
  4894.7 1918.60  4910.0 1918.51  4915.9 1916.51  4968.0 1919.74  5003.2 1919.03
  5011.0 1916.44  5022.4 1915.78  5022.9 1915.28  5028.1 1915.78  5046.1 1919.46
  5188.0 1921.38  5542.5 1922.21  5619.6 1922.13  6107.5 1923.09  6117.7 1922.93
  6268.8 1923.55  6350.7 1923.89  6392.1 1924.55  6521.5 1925.07  6749.6 1928.15
  6891.5 1932.78  6899.3 1934.61  6905.8 1932.97  7004.7 1935.77  7019.7 1935.67
#Mann=12,-1,0
  4524.0    0.07       0  5022.4    0.07       0  5028.1    0.07       0
  5542.5    0.16       0  5619.6    0.07       0  6107.5    0.16       0
  6117.7    0.07       0  6268.8    0.16       0  6350.7    0.07       0
  6392.1    0.16       0  6521.5    0.07       0  7004.7   0.035       0
Bank Sta=5022.4,5028.1
Exp/Cntr=0.3,0.1

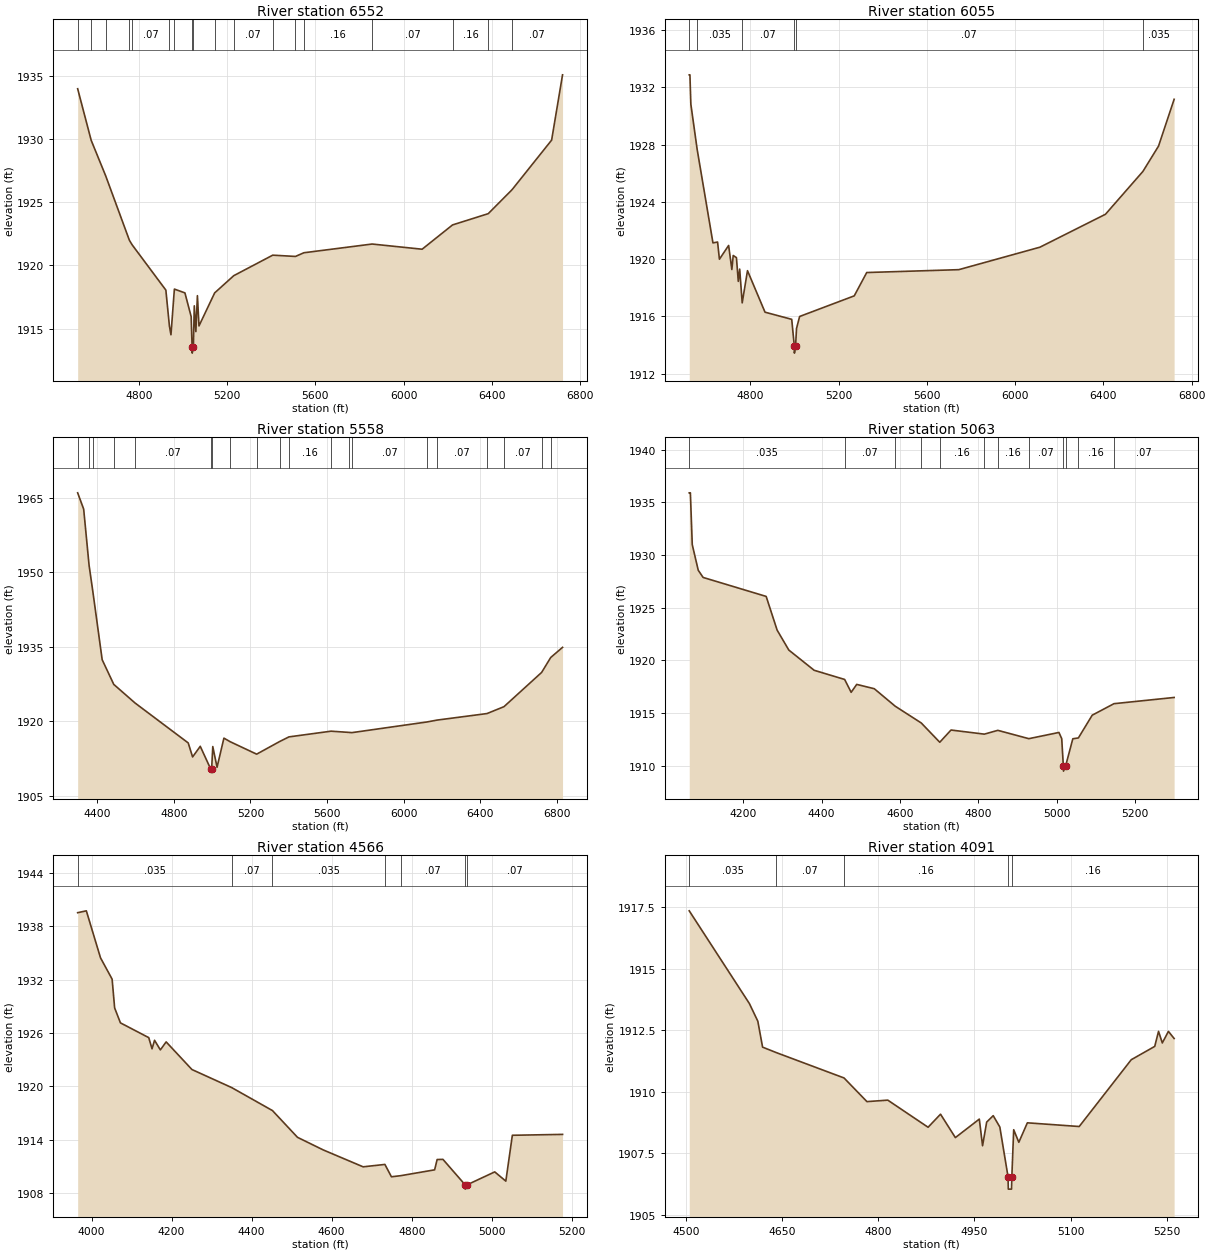
Type RM Length L Ch R = 1,6552,497,497,497
BEGIN DESCRIPTION:
Stink Creek Trib4 5.0
END DESCRIPTION:
XS GIS Cut Line= 3
      1433054.98      6874288.03      1433338.43      6873904.88
      1434554.99      6872688.01
#Sta/Elev= 30
  4523.4 1933.96  4584.6 1929.89  4650.4 1927.08  4757.8 1921.99  4769.8 1921.64
  4923.1 1918.05  4939.2 1915.21  4946.2 1914.52  4961.7 1918.13  5009.5 1917.83
  5037.8 1915.95  5042.0 1913.57  5042.5 1913.07  5047.7 1913.57  5051.9 1916.81
  5059.0 1914.77  5066.1 1917.61  5073.2 1915.22  5144.3 1917.83  5230.8 1919.19
  5407.4 1920.81  5510.3 1920.71  5548.5 1921.00  5857.8 1921.69  6084.3 1921.28
  6222.2 1923.20  6384.0 1924.09  6491.7 1925.98  6671.2 1929.90  6720.7 1935.06
#Mann=18,-1,0
  4523.4    0.07       0  4584.6   0.035       0  4650.4    0.07       0
  4757.8   0.035       0  4769.8    0.07       0  4939.2    0.16       0
  4961.7    0.07       0  5042.0    0.07       0  5047.7    0.07       0
  5144.3    0.16       0  5230.8    0.07       0  5407.4    0.16       0
  5510.3    0.07       0  5548.5    0.16       0  5857.8    0.07       0
  6222.2    0.16       0  6384.0   0.035       0  6491.7    0.07       0
Bank Sta=5042,5047.7
Exp/Cntr=0.3,0.1

Type RM Length L Ch R = 1,6055,497,497,497
BEGIN DESCRIPTION:
Stink Creek Trib4 4.0
END DESCRIPTION:
XS GIS Cut Line= 3
      1433155.00      6874488.00      1433538.24      6874204.52
      1434755.01      6872987.99
#Sta/Elev= 30
  4523.3 1932.87  4526.4 1932.87  4530.6 1930.82  4559.2 1927.66  4630.8 1921.13
  4651.7 1921.19  4660.1 1919.99  4701.8 1920.95  4716.4 1919.27  4722.6 1920.25
  4737.2 1920.10  4745.6 1918.44  4751.9 1919.30  4763.3 1916.94  4787.3 1919.19
  4866.7 1916.29  4987.7 1915.79  4999.4 1913.93  4999.9 1913.43  5005.2 1913.93
  5009.4 1915.15  5023.5 1915.99  5271.0 1917.43  5327.6 1919.06  5744.8 1919.26
  6112.5 1920.83  6409.5 1923.13  6579.0 1926.12  6649.9 1927.89  6720.6 1931.16
#Mann=6,-1,0
  4523.3    0.07       0  4559.2   0.035       0  4763.3    0.07       0
  4999.4    0.07       0  5005.2    0.07       0  6579.0   0.035       0
Bank Sta=4999.4,5005.2
Exp/Cntr=0.3,0.1

Type RM Length L Ch R = 1,5558,495,495,495
BEGIN DESCRIPTION:
Stink Creek Trib4 3.0
END DESCRIPTION:
XS GIS Cut Line= 3
      1433104.99      6874788.00      1433739.79      6874488.51
      1434855.02      6873037.97
#Sta/Elev= 30
  4298.1 1966.02  4329.5 1962.74  4357.8 1951.39  4376.2 1946.46  4426.1 1932.39
  4486.6 1927.42  4598.0 1923.66  4875.4 1915.62  4898.2 1912.80  4938.2 1914.94
  4991.8 1910.44  4992.3 1909.94  4997.7 1910.44  5003.6 1914.89  5025.9 1910.72
  5061.7 1916.59  5094.8 1915.86  5232.6 1913.36  5353.0 1915.91  5401.3 1916.84
  5621.4 1917.99  5715.8 1917.74  5730.6 1917.70  6122.5 1919.85  6173.9 1920.22
  6435.3 1921.54  6524.0 1922.93  6720.5 1929.83  6768.0 1932.84  6829.7 1934.88
#Mann=20,-1,0
  4298.1    0.07       0  4357.8   0.035       0  4376.2    0.07       0
  4486.6   0.035       0  4598.0    0.07       0  4991.8    0.07       0
  4997.7    0.07       0  5094.8    0.16       0  5232.6    0.16       0
  5353.0    0.07       0  5401.3    0.16       0  5621.4    0.07       0
  5715.8    0.16       0  5730.6    0.07       0  6122.5   0.035       0
  6173.9    0.07       0  6435.3   0.035       0  6524.0    0.07       0
  6720.5   0.035       0  6768.0    0.07       0
Bank Sta=4991.8,4997.7
Exp/Cntr=0.3,0.1

Type RM Length L Ch R = 1,5063,497,497,497
BEGIN DESCRIPTION:
Stink Creek Trib4 2.0
END DESCRIPTION:
XS GIS Cut Line= 3
      1433555.00      6875238.00      1434052.84      6874443.48
      1434264.11      6874231.62
#Sta/Elev= 30
  4062.4 1935.91  4065.3 1935.91  4070.1 1930.99  4085.4 1928.56  4097.8 1927.88
  4258.6 1926.08  4286.6 1922.88  4316.4 1920.99  4381.0 1919.07  4458.8 1918.20
  4475.4 1916.98  4489.6 1917.73  4534.4 1917.32  4587.8 1915.66  4654.2 1914.07
  4701.4 1912.24  4730.1 1913.40  4815.0 1913.01  4849.5 1913.37  4928.6 1912.58
  5005.4 1913.17  5012.5 1912.58  5016.6 1910.00  5017.1 1909.50  5022.5 1910.00
  5040.8 1912.57  5055.0 1912.65  5090.3 1914.81  5145.8 1915.90  5299.2 1916.49
#Mann=12,-1,0
  4062.4   0.035       0  4458.8    0.07       0  4587.8    0.16       0
  4654.2   0.035       0  4701.4    0.16       0  4815.0    0.07       0
  4849.5    0.16       0  4928.6    0.07       0  5016.6    0.07       0
  5022.5    0.07       0  5055.0    0.16       0  5145.8    0.07       0
Bank Sta=5016.6,5022.5
Exp/Cntr=0.3,0.1

Type RM Length L Ch R = 1,4566,475,475,475
BEGIN DESCRIPTION:
Stink Creek Trib4 1.0
END DESCRIPTION:
XS GIS Cut Line= 3
      1433555.03      6875287.97      1434375.60      6874657.84
      1434458.60      6874501.73
#Sta/Elev= 30
  3965.4 1939.53  3987.1 1939.74  4022.5 1934.45  4051.5 1932.05  4057.8 1928.81
  4072.3 1927.13  4143.0 1925.47  4151.2 1924.21  4157.5 1925.17  4172.0 1924.09
  4186.5 1924.99  4250.9 1921.88  4350.1 1919.85  4452.1 1917.26  4514.6 1914.25
  4579.0 1912.83  4678.6 1910.93  4733.0 1911.20  4749.3 1909.81  4772.1 1909.93
  4857.2 1910.59  4863.5 1911.75  4878.0 1911.77  4933.1 1908.92  4933.6 1908.42
  4939.0 1908.92  5007.4 1910.36  5035.1 1909.32  5051.4 1914.48  5176.8 1914.58
#Mann=7,-1,0
  3965.4   0.035       0  4350.1    0.07       0  4452.1   0.035       0
  4733.0    0.16       0  4772.1    0.07       0  4933.1    0.07       0
  4939.0    0.07       0
Bank Sta=4933.1,4939
Exp/Cntr=0.3,0.1

Type RM Length L Ch R = 1,4091,923,923,923
BEGIN DESCRIPTION:
Stink Creek Trib4 0.4
END DESCRIPTION:
XS GIS Cut Line= 3
      1434023.72      6875136.84      1434505.23      6875024.23
      1434642.80      6874802.31
#Sta/Elev= 30
  4505.5 1917.34  4599.2 1913.58  4612.4 1912.86  4619.8 1911.81  4641.0 1911.59
  4746.7 1910.56  4782.4 1909.60  4814.9 1909.66  4877.7 1908.56  4897.1 1909.09
  4920.2 1908.14  4957.5 1908.89  4962.6 1907.81  4969.0 1908.77  4979.2 1909.03
  4989.5 1908.57  5002.3 1906.55  5002.7 1906.05  5007.7 1906.05  5008.2 1906.55
  5011.1 1908.46  5019.1 1907.95  5032.4 1908.74  5113.2 1908.59  5194.3 1911.30
  5230.9 1911.84  5236.8 1912.45  5242.7 1911.98  5252.2 1912.45  5261.1 1912.16
#Mann=5,-1,0
  4505.5   0.035       0  4641.0    0.07       0  4746.7    0.16       0
  5002.3    0.07       0  5008.2    0.16       0
Bank Sta=5002.3,5008.2
Exp/Cntr=0.3,0.1

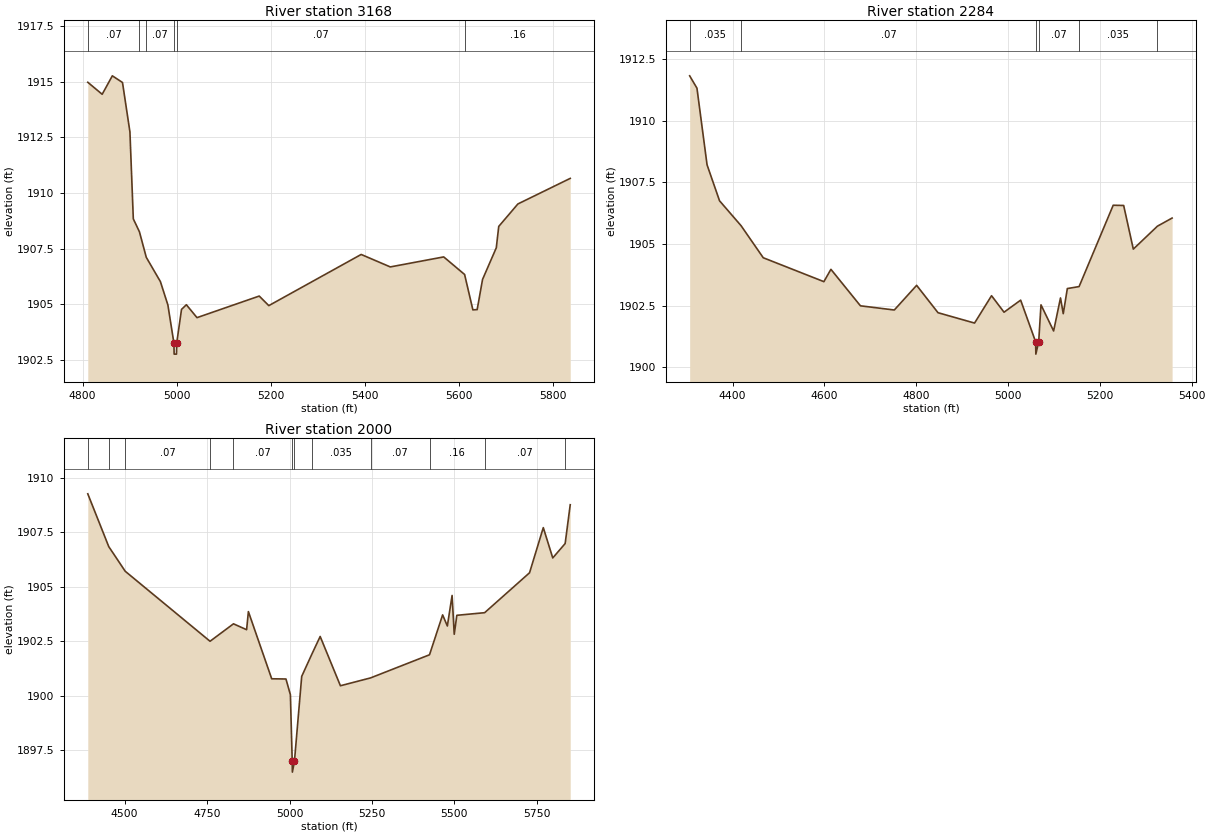
Type RM Length L Ch R = 1,3168,884,884,884
BEGIN DESCRIPTION:
Stink Creek Trib4 0.3
END DESCRIPTION:
XS GIS Cut Line= 3
      1434576.17      6875902.01      1434670.06      6875737.86
      1434878.27      6874927.48
#Sta/Elev= 30
  4810.9 1914.98  4841.5 1914.44  4863.1 1915.27  4884.7 1914.97  4900.5 1912.75
  4907.7 1908.84  4920.7 1908.26  4935.3 1907.11  4965.3 1906.02  4981.2 1904.97
  4994.0 1903.26  4994.5 1902.76  4999.5 1902.76  5000.0 1903.26  5010.2 1904.77
  5020.5 1904.98  5043.1 1904.40  5175.4 1905.37  5195.8 1904.94  5392.2 1907.24
  5454.1 1906.68  5567.7 1907.13  5612.1 1906.34  5629.7 1904.75  5638.8 1904.76
  5650.3 1906.12  5679.5 1907.54  5684.7 1908.50  5725.4 1909.51  5836.7 1910.66
#Mann=6,-1,0
  4810.9    0.07       0  4920.7   0.035       0  4935.3    0.07       0
  4994.0    0.07       0  5000.0    0.07       0  5612.1    0.16       0
Bank Sta=4994,5000
Exp/Cntr=0.3,0.1

Type RM Length L Ch R = 1,2284,284,284,284
BEGIN DESCRIPTION:
Stink Creek Trib4 0.2
END DESCRIPTION:
XS GIS Cut Line= 3
      1434781.34      6876064.81      1435375.64      6875707.38
      1435576.81      6875411.97
#Sta/Elev= 30
  4306.5 1911.82  4322.4 1911.32  4344.4 1908.21  4371.6 1906.75  4418.5 1905.74
  4466.8 1904.44  4598.9 1903.47  4614.2 1903.97  4678.5 1902.49  4752.3 1902.32
  4800.9 1903.32  4847.5 1902.21  4927.1 1901.79  4964.1 1902.90  4991.3 1902.23
  5027.5 1902.72  5060.1 1901.03  5060.6 1900.53  5066.8 1901.03  5071.8 1902.53
  5099.3 1901.47  5114.3 1902.81  5120.3 1902.17  5129.2 1903.19  5154.8 1903.27
  5229.1 1906.57  5251.9 1906.56  5272.9 1904.79  5325.4 1905.72  5357.4 1906.05
#Mann=6,-1,0
  4306.5   0.035       0  4418.5    0.07       0  5060.1    0.07       0
  5066.8    0.07       0  5154.8   0.035       0  5325.4    0.07       0
Bank Sta=5060.1,5066.8
Exp/Cntr=0.3,0.1

Type RM Length L Ch R = 1,2000,0,0,0
BEGIN DESCRIPTION:
Stink Creek Trib4 0.1
END DESCRIPTION:
XS GIS Cut Line= 4
      1434889.12      6876198.11      1435454.94      6875965.44
      1435647.22      6875896.13      1436149.43      6875488.19
#Sta/Elev= 30
  4388.2 1909.26  4451.8 1906.84  4501.7 1905.71  4759.0 1902.50  4830.1 1903.30
  4869.9 1903.03  4875.3 1903.86  4946.0 1900.78  4989.2 1900.77  5002.7 1900.05
  5008.2 1897.00  5008.7 1896.50  5015.0 1897.00  5037.0 1900.89  5066.9 1901.88
  5093.0 1902.72  5154.4 1900.46  5245.9 1900.82  5424.6 1901.88  5464.4 1903.71
  5478.7 1903.20  5493.1 1904.60  5499.6 1902.82  5507.5 1903.69  5591.8 1903.81
  5728.0 1905.64  5769.7 1907.71  5798.4 1906.32  5836.0 1906.98  5851.4 1908.76
#Mann=12,-1,0
  4388.2    0.07       0  4451.8   0.035       0  4501.7    0.07       0
  4759.0   0.035       0  4830.1    0.07       0  5008.2    0.07       0
  5015.0    0.07       0  5066.9   0.035       0  5245.9    0.07       0
  5424.6    0.16       0  5591.8    0.07       0  5836.0   0.035       0
Bank Sta=5008.2,5015
Exp/Cntr=0.3,0.1

Chan Stop Cuts=-1