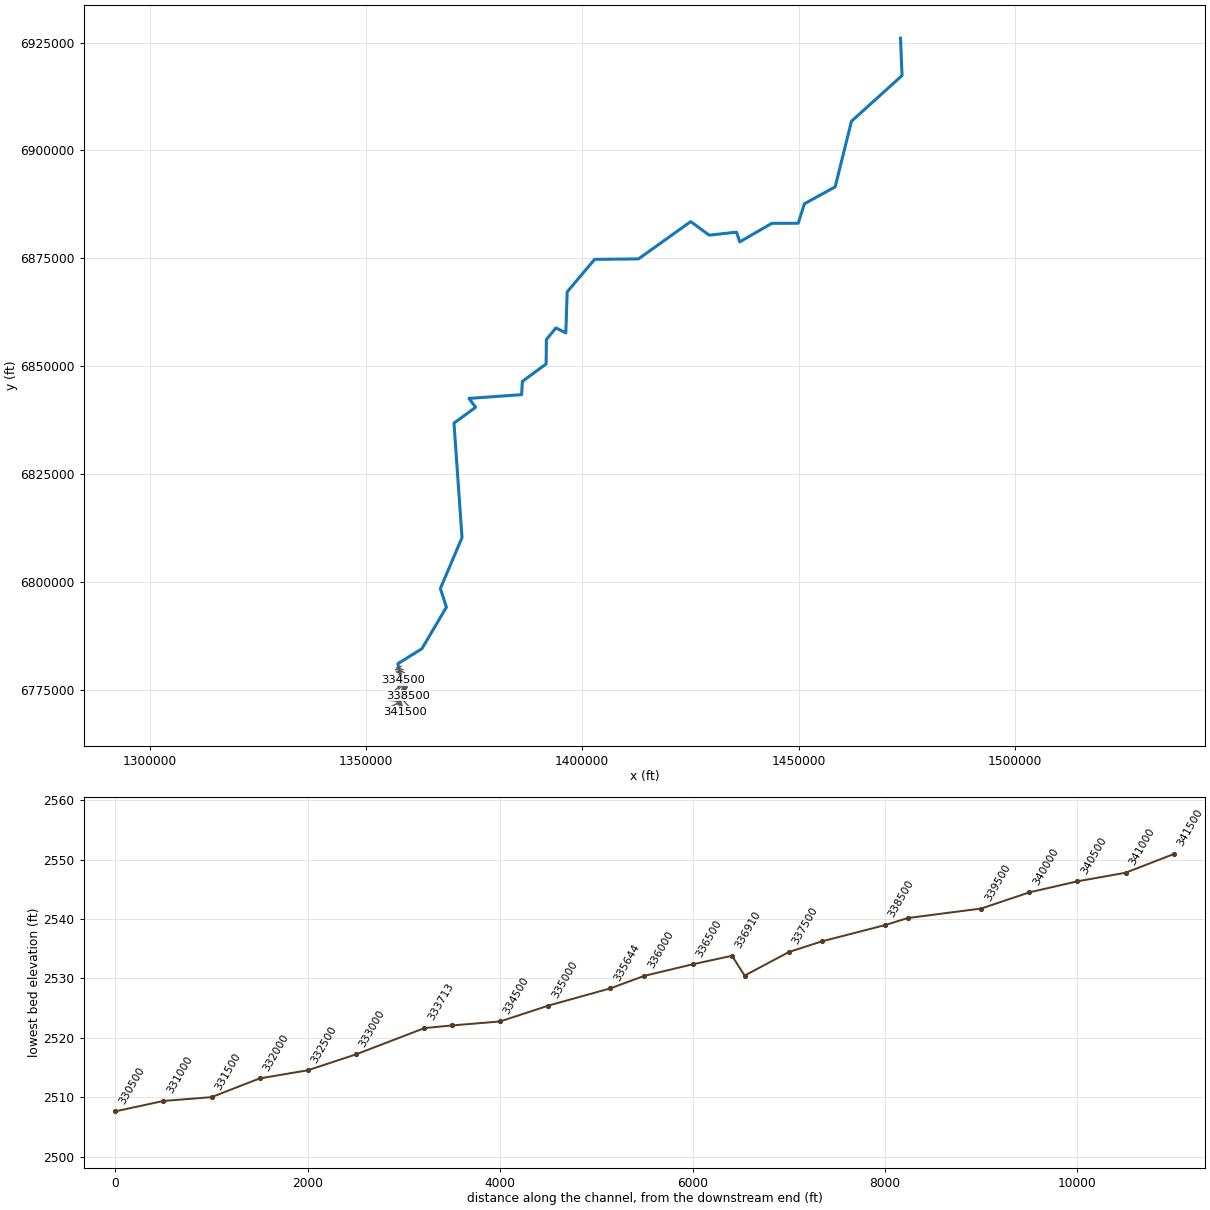
--- Sweetwater Creek.prj (project) ---

Proj Title=Sweetwater Creek Base Level Engineering
Current Plan=p01
Default Exp/Contr=0.3,0.1
English Units
Geom File=g01
Flow File=f01
Plan File=p01
BEGIN DESCRIPTION:
Sweetwater Creek
END DESCRIPTION:

--- Sweetwater Creek.p01 (plan) ---

Plan Title=Multiple Run
Short Identifier=Multiple
Geom File=g01
Flow File=f01
Subcritical Flow
K Sum by GR= 0
Std Step Tol= 0.01
Critical Tol= 0.01
Num of Std Step Trials= 20
Max Error Tol= 0.3
Flow Tol Ratio= 0.001
Split Flow NTrial= 30
Split Flow Tol= 0.02
Split Flow Ratio= 0.02
Log Output Level= 0
Friction Slope Method= 1
Unsteady Friction Slope Method= 2
Unsteady Bridges Friction Slope Method= 1
Parabolic Critical Depth
Global Vel Dist=  1 , 1 , 1
Global Log Level= 0
CheckData=True
Encroach Param= -1, 0, 0, 0
BEGIN DESCRIPTION:
Multiple Run
END DESCRIPTION:

--- Sweetwater Creek.f01 (steady flow) ---

Flow Title=Multiple
Number of Profiles=7
Profile Names=10-year,25-year,50-year,1pct_min,100-year,1pct_plu,500-year
River Rch & RM= Sweetwater Creek,Reach-1,341500
     210     290     356     217     434     866     651
River Rch & RM= Sweetwater Creek,Reach-1,341000
     278     389     481     296     590    1177     898
River Rch & RM= Sweetwater Creek,Reach-1,337500
     441     627     782     483     964    1923    1487
River Rch & RM= Sweetwater Creek,Reach-1,332500
     492     704     882     548    1093    2180    1701
River Rch & RM= Sweetwater Creek,Reach-1,329500
    1005    1481    1894    1197    2389    4767    3857
River Rch & RM= Sweetwater Creek,Reach-1,325500
    1097    1625    2085    1323    2640    5268    4293
River Rch & RM= Sweetwater Creek,Reach-1,320193
    1565    2353    3050    1954    3899    7780    6463
River Rch & RM= Sweetwater Creek,Reach-1,311500
    1668    2521    3279    2108    4206    8391    7017
River Rch & RM= Sweetwater Creek,Reach-1,305500
    1937    2947    3852    2487    4963    9902    8354
River Rch & RM= Sweetwater Creek,Reach-1,299000
    2341    3585    4709    3054    6094   12159   10349
River Rch & RM= Sweetwater Creek,Reach-1,297500
    2512    3859    5080    3302    6588   13145   11236
River Rch & RM= Sweetwater Creek,Reach-1,293000
    2556    3929    5173    3364    6711   13390   11451
River Rch & RM= Sweetwater Creek,Reach-1,292500
    2643    4072    5370    3497    6978   13922   11944
River Rch & RM= Sweetwater Creek,Reach-1,288500
    2860    4416    5834    3805    7592   15149   13037
River Rch & RM= Sweetwater Creek,Reach-1,285000
    3039    4700    6215    4058    8096   16154   13927
River Rch & RM= Sweetwater Creek,Reach-1,283000
    3298    5115    6778    4434    8848   17654   15279
River Rch & RM= Sweetwater Creek,Reach-1,277000
    3301    5119    6784    4438    8854   17667   15289
River Rch & RM= Sweetwater Creek,Reach-1,275500
    3438    5339    7081    4636    9251   18457   16002
River Rch & RM= Sweetwater Creek,Reach-1,272143
    3456    5366    7115    4658    9294   18544   16069
River Rch & RM= Sweetwater Creek,Reach-1,270455
    3407    5280    6993    4572    9122   18202   15733
River Rch & RM= Sweetwater Creek,Reach-1,266000
    3469    5378    7125    4659    9296   18549   16040
River Rch & RM= Sweetwater Creek,Reach-1,265000
    3733    5809    7717    5059   10095   20141   17507
River Rch & RM= Sweetwater Creek,Reach-1,258938
    3744    5826    7738    5073   10123   20197   17554
River Rch & RM= Sweetwater Creek,Reach-1,257500
    3746    5829    7742    5076   10128   20207   17562
River Rch & RM= Sweetwater Creek,Reach-1,256500
    3817    5942    7893    5176   10327   20606   17914
River Rch & RM= Sweetwater Creek,Reach-1,256000
    3833    5964    7920    5192   10359   20669   17957
River Rch & RM= Sweetwater Creek,Reach-1,253000
    3843    5978    7939    5203   10381   20713   17990
River Rch & RM= Sweetwater Creek,Reach-1,250000
    3871    6024    8001    5245   10465   20881   18144
River Rch & RM= Sweetwater Creek,Reach-1,249000
    4479    6990    9304    6111   12194   24330   21219
River Rch & RM= Sweetwater Creek,Reach-1,242021
    4477    6986    9297    6106   12183   24308   21192
River Rch & RM= Sweetwater Creek,Reach-1,239327
    4998    7817   10422    6855   13678   27290   23865
River Rch & RM= Sweetwater Creek,Reach-1,235391
    5005    7827   10434    6862   13692   27319   23884
River Rch & RM= Sweetwater Creek,Reach-1,231000
    5010    7833   10441    6866   13700   27335   23894
River Rch & RM= Sweetwater Creek,Reach-1,230374
    4987    7788   10374    6817   13602   27140   23687
River Rch & RM= Sweetwater Creek,Reach-1,222406
    5129    8016   10681    7021   14009   27952   24412
River Rch & RM= Sweetwater Creek,Reach-1,221500
    5588    8746   11668    7679   15321   30569   26751
River Rch & RM= Sweetwater Creek,Reach-1,216000
    5771    9036   12057    7936   15835   31596   27661
River Rch & RM= Sweetwater Creek,Reach-1,213500
    5807    9093   12135    7988   15939   31802   27845
River Rch & RM= Sweetwater Creek,Reach-1,213000
    5806    9088   12126    7980   15922   31769   27802
River Rch & RM= Sweetwater Creek,Reach-1,209500
    5809    9092   12131    7983   15928   31781   27809
River Rch & RM= Sweetwater Creek,Reach-1,207500
    5798    9064   12082    7944   15850   31625   27622
River Rch & RM= Sweetwater Creek,Reach-1,200500
    5789    9047   12058    7926   15814   31554   27548
River Rch & RM= Sweetwater Creek,Reach-1,199382
    6223    9697   12902    8467   16894   33708   29313
River Rch & RM= Sweetwater Creek,Reach-1,196500
    6161    9587   12743    8355   16670   33262   28868
River Rch & RM= Sweetwater Creek,Reach-1,190097
    6172    9600   12759    8363   16687   33295   28884
River Rch & RM= Sweetwater Creek,Reach-1,187000
    6153    9567   12712    8330   16622   33164   28755
River Rch & RM= Sweetwater Creek,Reach-1,186000
    6166    9581   12724    8334   16628   33177   28736
River Rch & RM= Sweetwater Creek,Reach-1,181000
    6216    9656   12822    8396   16753   33426   28940
River Rch & RM= Sweetwater Creek,Reach-1,177500
    6170    9573   12701    8310   16581   33083   28592
River Rch & RM= Sweetwater Creek,Reach-1,172334
    7808   12163   16187   10621   21191   42283   36739
River Rch & RM= Sweetwater Creek,Reach-1,171074
    7819   12178   16204   10631   21211   42321   36761
River Rch & RM= Sweetwater Creek,Reach-1,170000
    7753   12059   16032   10508   20967   41835   36274
River Rch & RM= Sweetwater Creek,Reach-1,162500
    7736   12030   15990   10479   20908   41718   36158
River Rch & RM= Sweetwater Creek,Reach-1,160889
    7988   12429   16528   10836   21620   43138   37416
River Rch & RM= Sweetwater Creek,Reach-1,158500
    7978   12410   16498   10813   21575   43048   37320
River Rch & RM= Sweetwater Creek,Reach-1,157500
    7975   12401   16484   10803   21555   43008   37274
River Rch & RM= Sweetwater Creek,Reach-1,155000
    7968   12388   16465   10789   21527   42952   37217
River Rch & RM= Sweetwater Creek,Reach-1,154285
    8000   12435   16524   10825   21600   43097   37328
River Rch & RM= Sweetwater Creek,Reach-1,149076
    7990   12415   16494   10803   21555   43008   37233
River Rch & RM= Sweetwater Creek,Reach-1,146500
    8263   12839   17057   11172   22291   44477   38500
River Rch & RM= Sweetwater Creek,Reach-1,144500
    8281   12868   17095   11197   22341   44576   38586
River Rch & RM= Sweetwater Creek,Reach-1,142000
    8273   12852   17073   11181   22308   44511   38517
River Rch & RM= Sweetwater Creek,Reach-1,138500
    8279   12860   17081   11185   22317   44529   38526
River Rch & RM= Sweetwater Creek,Reach-1,137500
    8247   12803   17000   11128   22203   44301   38301
River Rch & RM= Sweetwater Creek,Reach-1,131569
    8250   12805   17000   11126   22199   44292   38279
River Rch & RM= Sweetwater Creek,Reach-1,130555
    8211   12736   16900   11055   22058   44012   38001
River Rch & RM= Sweetwater Creek,Reach-1,126000
   11316   17616   23448   15384   30694   61243   53157
River Rch & RM= Sweetwater Creek,Reach-1,118856
   11315   17601   23417   15355   30638   61130   53004
River Rch & RM= Sweetwater Creek,Reach-1,113500
   11255   17489   23250   15234   30396   60647   52502
River Rch & RM= Sweetwater Creek,Reach-1,105000
   11239   17461   23209   15205   30337   60531   52385
River Rch & RM= Sweetwater Creek,Reach-1,102000
   11272   17510   23272   15244   30417   60689   52511
River Rch & RM= Sweetwater Creek,Reach-1,100500
   11673   18124   24083   15772   31470   62790   54297
River Rch & RM= Sweetwater Creek,Reach-1,92500
   11667   18111   24062   15755   31436   62723   54221
River Rch & RM= Sweetwater Creek,Reach-1,90500
   11553   17912   23778   15556   31039   61930   53444
River Rch & RM= Sweetwater Creek,Reach-1,80500
   11531   17871   23717   15513   30952   61757   53266
River Rch & RM= Sweetwater Creek,Reach-1,74000
   11607   18001   23901   15640   31205   62263   53753
River Rch & RM= Sweetwater Creek,Reach-1,73000
   12164   18792   24893   16251   32425   64697   55559
River Rch & RM= Sweetwater Creek,Reach-1,67087
   12128   18727   24798   16183   32290   64427   55287
River Rch & RM= Sweetwater Creek,Reach-1,64000
   12109   18684   24731   16132   32187   64221   55057
River Rch & RM= Sweetwater Creek,Reach-1,57500
   12065   18599   24603   16038   32000   63849   54668
River Rch & RM= Sweetwater Creek,Reach-1,47000
   12068   18601   24602   16035   31995   63838   54646
River Rch & RM= Sweetwater Creek,Reach-1,45000
   11996   18472   24413   15901   31726   63302   54105
River Rch & RM= Sweetwater Creek,Reach-1,33446
   11946   18383   24286   15811   31547   62944   53752
River Rch & RM= Sweetwater Creek,Reach-1,3000
   11947   18329   24165   15699   31324   62500   53144
Boundary for River Rch & Prof#=Sweetwater Creek,Reach-1,1
Up Type=0
Dn Type=3
Dn Slope=0.004
Boundary for River Rch & Prof#=Sweetwater Creek,Reach-1,2
Up Type=0
Dn Type=3
Dn Slope=0.004
Boundary for River Rch & Prof#=Sweetwater Creek,Reach-1,3
Up Type=0
Dn Type=3
Dn Slope=0.004
Boundary for River Rch & Prof#=Sweetwater Creek,Reach-1,4
Up Type=0
Dn Type=3
Dn Slope=0.004
Boundary for River Rch & Prof#=Sweetwater Creek,Reach-1,5
Up Type=0
Dn Type=3
Dn Slope=0.004
Boundary for River Rch & Prof#=Sweetwater Creek,Reach-1,6
Up Type=0
Dn Type=3
Dn Slope=0.004
Boundary for River Rch & Prof#=Sweetwater Creek,Reach-1,7
Up Type=0
Dn Type=3
Dn Slope=0.004

--- Sweetwater Creek.g01 (geometry) ---

Geom Title=Existing Conditions

River Reach=Sweetwater Creek,Reach-1
Reach XY= 30
      1357355.00      6771788.00      1359155.49      6774072.80
      1357360.14      6780990.59      1362941.38      6784474.76
      1368603.24      6794094.08      1367206.20      6798427.50
      1372205.54      6810217.56      1370355.24      6836772.78
      1375349.49      6840435.56      1373815.78      6842497.68
      1385988.38      6843371.29      1386165.77      6846447.70
      1391651.45      6850489.47      1391705.00      6856138.00
      1393906.22      6858834.57      1396199.54      6857685.55
      1396508.53      6867186.53      1402852.71      6874732.16
      1413003.53      6874841.55      1425065.47      6883487.47
      1429321.00      6880338.23      1435653.97      6881034.54
      1436389.67      6878787.21      1443811.08      6883086.43
      1449918.34      6883101.36      1451327.84      6887611.86
      1458449.48      6891535.56      1462212.86      6906744.17
      1473902.09      6917345.91      1473555.00      6925988.00

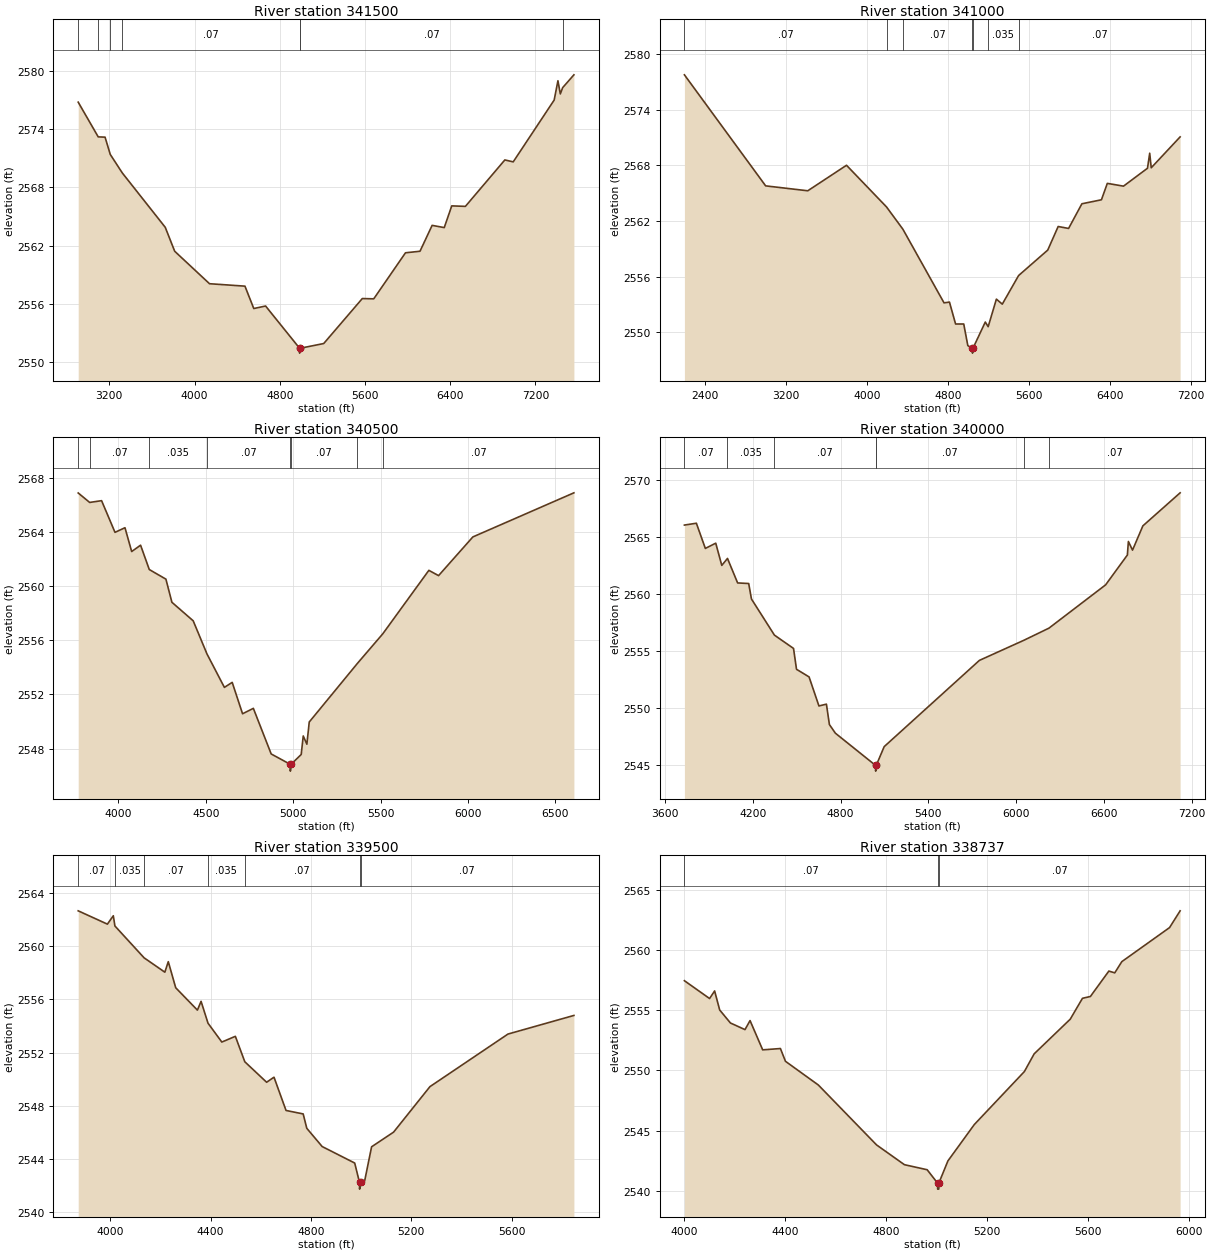
Type RM Length L Ch R = 1,341500,500,500,500
BEGIN DESCRIPTION:
Sweetwater Creek 681.0
END DESCRIPTION:
XS GIS Cut Line= 3
      1355505.02      6770888.01      1357364.59      6771845.94
      1358955.01      6769837.99
#Sta/Elev= 30
  2908.2 2576.80  3096.0 2573.22  3160.3 2573.19  3209.2 2571.41  3322.1 2569.50
  3725.4 2563.89  3814.0 2561.42  4140.9 2558.07  4473.4 2557.82  4556.5 2555.51
  4667.3 2555.77  4986.6 2551.41  4986.8 2550.91  4990.6 2551.41  5213.0 2551.90
  5575.1 2556.54  5682.5 2556.51  5980.5 2561.26  6116.8 2561.42  6230.6 2564.09
  6344.4 2563.86  6414.8 2566.10  6543.0 2566.05  6913.2 2570.84  6991.8 2570.64
  7376.4 2577.02  7411.6 2579.01  7433.9 2577.65  7456.2 2578.30  7561.5 2579.62
#Mann=7,-1,0
  2908.2   0.035       0  3096.0    0.07       0  3209.2   0.035       0
  3322.1    0.07       0  4986.6    0.07       0  4990.6    0.07       0
  7456.2   0.035       0
Bank Sta=4986.6,4990.6
Exp/Cntr=0.3,0.1

Type RM Length L Ch R = 1,341000,500,500,500
BEGIN DESCRIPTION:
Sweetwater Creek 680.0
END DESCRIPTION:
XS GIS Cut Line= 3
      1354854.96      6772588.01      1357638.51      6772222.08
      1358654.99      6770388.03
#Sta/Elev= 30
  2192.5 2577.77  2996.3 2565.80  3413.0 2565.27  3796.2 2568.02  4192.0 2563.53
  4353.9 2561.13  4761.1 2553.19  4814.9 2553.27  4875.4 2550.91  4956.1 2550.91
  4996.5 2548.58  5042.5 2548.27  5042.8 2547.77  5046.5 2548.27  5169.3 2551.12
  5197.9 2550.62  5279.1 2553.59  5337.5 2553.05  5498.6 2556.13  5787.4 2558.88
  5890.4 2561.42  5993.5 2561.21  6125.1 2563.87  6318.5 2564.30  6376.6 2566.07
  6536.7 2565.77  6774.1 2567.70  6795.9 2569.32  6811.1 2567.75  7096.9 2571.08
#Mann=7,-1,0
  2192.5    0.07       0  4192.0   0.035       0  4353.9    0.07       0
  5042.5    0.07       0  5046.5    0.07       0  5197.9   0.035       0
  5498.6    0.07       0
Bank Sta=5042.5,5046.5
Exp/Cntr=0.3,0.1

Type RM Length L Ch R = 1,340500,500,500,500
BEGIN DESCRIPTION:
Sweetwater Creek 679.0
END DESCRIPTION:
XS GIS Cut Line= 3
      1356955.04      6772937.98      1358057.67      6772394.04
      1358455.01      6770837.97
#Sta/Elev= 30
  3770.5 2566.89  3836.1 2566.19  3904.3 2566.32  3981.0 2563.98  4038.1 2564.32
  4076.4 2562.56  4127.3 2563.03  4177.1 2561.23  4272.2 2560.52  4306.5 2558.81
  4428.3 2557.44  4507.2 2554.99  4606.7 2552.52  4651.4 2552.89  4710.6 2550.57
  4772.4 2550.97  4874.4 2547.60  4983.8 2546.83  4984.1 2546.33  4987.9 2546.83
  5046.1 2547.56  5057.8 2548.93  5078.5 2548.32  5092.1 2549.96  5368.1 2554.30
  5512.8 2556.48  5776.3 2561.17  5831.9 2560.78  6028.0 2563.64  6606.0 2566.90
#Mann=8,-1,0
  3770.5   0.035       0  3836.1    0.07       0  4177.1   0.035       0
  4507.2    0.07       0  4983.8    0.07       0  4987.9    0.07       0
  5368.1   0.035       0  5512.8    0.07       0
Bank Sta=4983.8,4987.9
Exp/Cntr=0.3,0.1

Type RM Length L Ch R = 1,340000,500,500,500
BEGIN DESCRIPTION:
Sweetwater Creek 678.0
END DESCRIPTION:
XS GIS Cut Line= 3
      1357104.95      6773038.01      1358345.85      6772777.25
      1359804.97      6771238.03
#Sta/Elev= 30
  3732.0 2566.07  3813.8 2566.23  3875.1 2564.02  3946.2 2564.48  3987.5 2562.53
  4026.5 2563.14  4095.8 2560.99  4171.4 2560.94  4190.4 2559.58  4347.3 2556.41
  4478.0 2555.24  4498.4 2553.41  4584.2 2552.74  4651.7 2550.19  4702.8 2550.35
  4723.2 2548.56  4764.1 2547.80  5039.1 2544.97  5039.4 2544.47  5043.2 2544.97
  5097.8 2546.62  5748.6 2554.19  6055.1 2555.97  6224.0 2557.02  6611.5 2560.82
  6760.3 2563.44  6767.2 2564.63  6795.5 2563.87  6866.3 2566.00  7120.9 2568.90
#Mann=7,-1,0
  3732.0    0.07       0  4026.5   0.035       0  4347.3    0.07       0
  5039.1    0.07       0  5043.2    0.07       0  6055.1   0.035       0
  6224.0    0.07       0
Bank Sta=5039.1,5043.2
Exp/Cntr=0.3,0.1

Type RM Length L Ch R = 1,339500,763,763,763
BEGIN DESCRIPTION:
Sweetwater Creek 677.0
END DESCRIPTION:
XS GIS Cut Line= 3
      1357535.46      6773538.49      1358578.32      6773110.16
      1359040.53      6772398.48
#Sta/Elev= 30
  3872.6 2562.66  3989.0 2561.66  4012.6 2562.29  4019.0 2561.52  4135.2 2559.13
  4218.0 2558.05  4231.7 2558.84  4261.3 2556.88  4347.8 2555.20  4362.4 2555.86
  4390.0 2554.22  4445.1 2552.80  4499.1 2553.23  4536.7 2551.32  4623.7 2549.78
  4653.1 2550.16  4701.1 2547.66  4769.4 2547.40  4783.8 2546.32  4845.1 2544.95
  4974.8 2543.71  4994.0 2542.25  4994.3 2541.75  4998.6 2542.25  5014.5 2542.37
  5042.1 2544.93  5129.7 2546.03  5274.7 2549.45  5585.7 2553.40  5848.6 2554.80
#Mann=7,-1,0
  3872.6    0.07       0  4019.0   0.035       0  4135.2    0.07       0
  4390.0   0.035       0  4536.7    0.07       0  4994.0    0.07       0
  4998.6    0.07       0
Bank Sta=4994,4998.6
Exp/Cntr=0.3,0.1

Type RM Length L Ch R = 1,338737,237,237,237
BEGIN DESCRIPTION:
Sweetwater Creek 676.0
END DESCRIPTION:
XS GIS Cut Line= 3
      1357985.57      6773599.28      1358982.16      6773564.41
      1359904.96      6773288.01
#Sta/Elev= 30
  4002.8 2557.45  4102.3 2555.97  4122.3 2556.60  4142.3 2555.02  4184.8 2553.94
  4242.4 2553.39  4262.4 2554.14  4312.4 2551.71  4382.5 2551.82  4402.5 2550.76
  4532.6 2548.79  4762.7 2543.82  4872.8 2542.18  4962.8 2541.76  5004.0 2540.65
  5004.4 2540.15  5008.7 2540.15  5009.1 2540.65  5044.9 2542.49  5149.3 2545.51
  5347.4 2549.91  5386.1 2551.38  5528.9 2554.26  5577.1 2555.99  5608.4 2556.14
  5681.5 2558.25  5704.8 2558.10  5732.6 2559.03  5921.6 2561.86  5963.3 2563.25
#Mann=3,-1,0
  4002.8    0.07       0  5004.0    0.07       0  5009.1    0.07       0
Bank Sta=5004,5009.1
Exp/Cntr=0.3,0.1

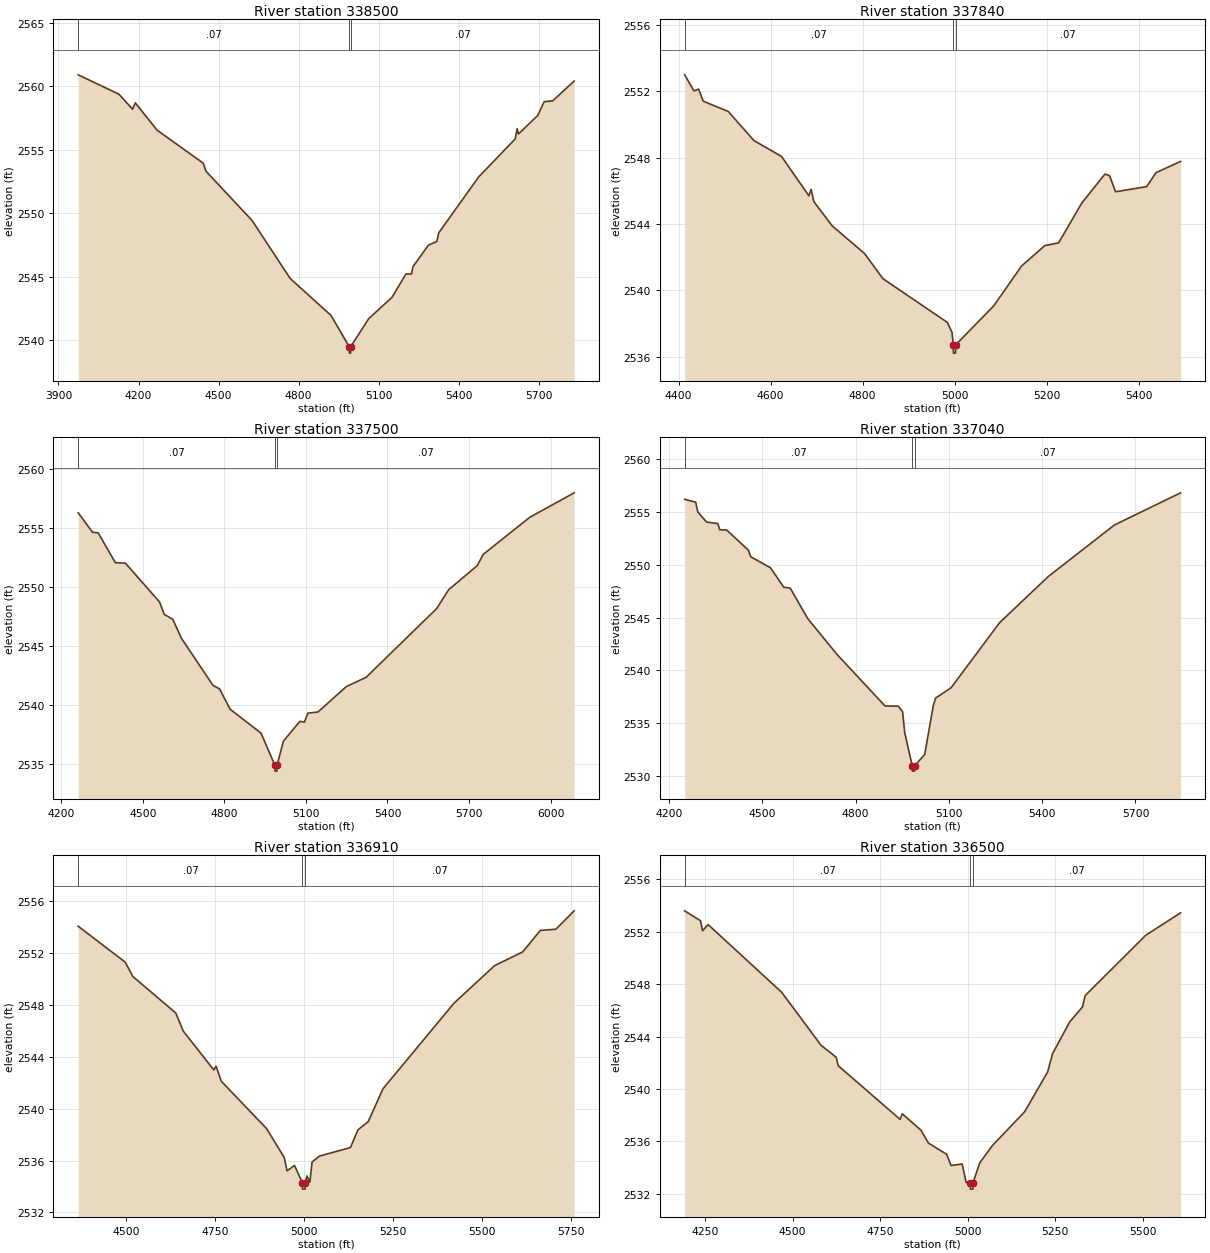
Type RM Length L Ch R = 1,338500,660,660,660
BEGIN DESCRIPTION:
Sweetwater Creek 675.0
END DESCRIPTION:
XS GIS Cut Line= 3
      1358005.00      6773988.00      1359012.38      6773792.87
      1359805.01      6773538.00
#Sta/Elev= 30
  3973.9 2560.92  4126.7 2559.39  4177.6 2558.21  4187.8 2558.71  4269.3 2556.56
  4442.5 2553.95  4452.6 2553.32  4625.8 2549.42  4768.4 2544.85  4921.2 2541.94
  4989.9 2539.46  4990.3 2538.96  4994.6 2538.96  4995.0 2539.46  5062.7 2541.68
  5149.8 2543.36  5202.3 2545.21  5223.2 2545.21  5228.4 2545.78  5286.4 2547.48
  5317.9 2547.77  5324.7 2548.44  5475.4 2552.88  5612.0 2555.87  5618.8 2556.67
  5624.0 2556.25  5696.0 2557.71  5720.3 2558.80  5752.4 2558.87  5832.6 2560.43
#Mann=3,-1,0
  3973.9    0.07       0  4989.9    0.07       0  4995.0    0.07       0
Bank Sta=4989.9,4995
Exp/Cntr=0.3,0.1

Type RM Length L Ch R = 1,337840,340,340,340
BEGIN DESCRIPTION:
Sweetwater Creek 674.0
END DESCRIPTION:
XS GIS Cut Line= 3
      1358524.78      6774418.23      1359110.68      6774385.64
      1359598.16      6774325.36
#Sta/Elev= 30
  4413.2 2552.99  4433.4 2552.02  4443.5 2552.13  4453.5 2551.40  4508.0 2550.78
  4563.6 2549.03  4623.7 2548.07  4683.1 2545.70  4688.1 2546.08  4693.9 2545.35
  4733.9 2543.88  4804.0 2542.22  4844.1 2540.70  4984.3 2538.06  4994.3 2537.46
  4997.1 2536.71  4997.5 2536.21  5001.9 2536.21  5002.3 2536.71  5085.0 2539.06
  5145.4 2541.46  5195.8 2542.69  5226.0 2542.86  5276.4 2545.26  5326.8 2547.01
  5336.9 2546.90  5349.7 2545.94  5417.5 2546.25  5437.6 2547.09  5491.2 2547.77
#Mann=3,-1,0
  4413.2    0.07       0  4997.1    0.07       0  5002.3    0.07       0
Bank Sta=4997.1,5002.3
Exp/Cntr=0.3,0.1

Type RM Length L Ch R = 1,337500,460,460,460
BEGIN DESCRIPTION:
Sweetwater Creek 673.0
END DESCRIPTION:
XS GIS Cut Line= 3
      1358354.99      6774438.00      1359054.82      6774672.87
      1359554.98      6775637.97
#Sta/Elev= 30
  4261.8 2556.30  4314.6 2554.65  4335.4 2554.60  4398.5 2552.07  4435.3 2552.04
  4561.4 2548.74  4578.3 2547.70  4609.9 2547.28  4641.5 2545.68  4757.6 2541.69
  4782.2 2541.38  4820.9 2539.66  4934.6 2537.64  4985.6 2534.92  4986.1 2534.42
  4993.1 2534.42  4993.6 2534.92  5017.0 2536.96  5077.7 2538.64  5094.2 2538.57
  5107.1 2539.33  5144.1 2539.43  5249.1 2541.59  5321.1 2542.36  5581.1 2548.19
  5625.3 2549.79  5730.3 2551.82  5752.5 2552.78  5923.9 2555.92  6087.0 2557.99
#Mann=3,-1,0
  4261.8    0.07       0  4985.6    0.07       0  4993.6    0.07       0
Bank Sta=4985.6,4993.6
Exp/Cntr=0.3,0.1

Type RM Length L Ch R = 1,337040,130,130,130
BEGIN DESCRIPTION:
Sweetwater Creek 672.0
END DESCRIPTION:
XS GIS Cut Line= 3
      1358255.01      6774538.01      1358807.73      6775044.52
      1359455.01      6775588.01
#Sta/Elev= 30
  4250.3 2556.19  4285.7 2555.91  4292.5 2554.99  4320.9 2554.03  4356.7 2553.89
  4363.4 2553.30  4385.0 2553.29  4455.3 2551.37  4462.7 2550.75  4526.2 2549.71
  4568.8 2547.87  4589.7 2547.78  4646.5 2544.88  4738.6 2541.56  4894.4 2536.63
  4936.9 2536.61  4951.1 2536.10  4957.9 2534.10  4982.2 2530.96  4982.7 2530.46
  4989.8 2530.46  4990.3 2530.96  5022.4 2532.05  5049.7 2536.65  5057.5 2537.38
  5107.0 2538.35  5263.1 2544.51  5419.2 2548.87  5632.5 2553.76  5845.2 2556.80
#Mann=3,-1,0
  4250.3    0.07       0  4982.2    0.07       0  4990.3    0.07       0
Bank Sta=4982.2,4990.3
Exp/Cntr=0.3,0.1

Type RM Length L Ch R = 1,336910,410,410,410
BEGIN DESCRIPTION:
Sweetwater Creek 4167
END DESCRIPTION:
XS GIS Cut Line= 3
      1358220.72      6774686.29      1358710.97      6775090.19
      1359314.31      6775551.51
#Sta/Elev= 30
  4364.8 2554.09  4497.3 2551.31  4518.1 2550.22  4639.3 2547.39  4660.2 2546.00
  4746.1 2543.00  4752.7 2543.29  4767.0 2542.13  4894.7 2538.47  4944.2 2536.24
  4952.1 2535.21  4972.9 2535.63  4995.3 2534.30  4995.8 2533.80  5002.9 2533.80
  5003.4 2534.30  5008.0 2534.82  5016.2 2534.33  5022.5 2535.89  5043.3 2536.35
  5130.5 2537.01  5151.3 2538.37  5180.4 2539.01  5222.0 2541.55  5421.5 2548.15
  5535.8 2551.05  5614.7 2552.11  5664.6 2553.77  5708.1 2553.86  5759.5 2555.28
#Mann=3,-1,0
  4364.8    0.07       0  4995.3    0.07       0  5003.4    0.07       0
Bank Sta=4995.3,5003.4
Exp/Cntr=0.3,0.1

Type RM Length L Ch R = 1,336500,500,500,500
BEGIN DESCRIPTION:
Sweetwater Creek 671.0
END DESCRIPTION:
XS GIS Cut Line= 3
      1358155.00      6774737.99      1358555.43      6775439.90
      1359055.01      6775788.01
#Sta/Elev= 30
  4191.9 2553.60  4237.3 2552.84  4243.0 2552.08  4258.9 2552.55  4469.2 2547.38
  4581.5 2543.34  4624.7 2542.43  4630.5 2541.78  4807.6 2537.68  4813.6 2538.11
  4866.7 2536.87  4888.3 2535.88  4940.2 2535.02  4953.1 2534.16  4984.8 2534.28
  4996.0 2532.87  5007.6 2532.86  5008.1 2532.36  5015.3 2532.36  5015.8 2532.86
  5035.2 2534.37  5070.9 2535.68  5163.4 2538.27  5228.9 2541.30  5243.2 2542.71
  5292.0 2545.12  5328.6 2546.27  5336.2 2547.13  5509.0 2551.73  5608.9 2553.45
#Mann=3,-1,0
  4191.9    0.07       0  5007.6    0.07       0  5015.8    0.07       0
Bank Sta=5007.6,5015.8
Exp/Cntr=0.3,0.1

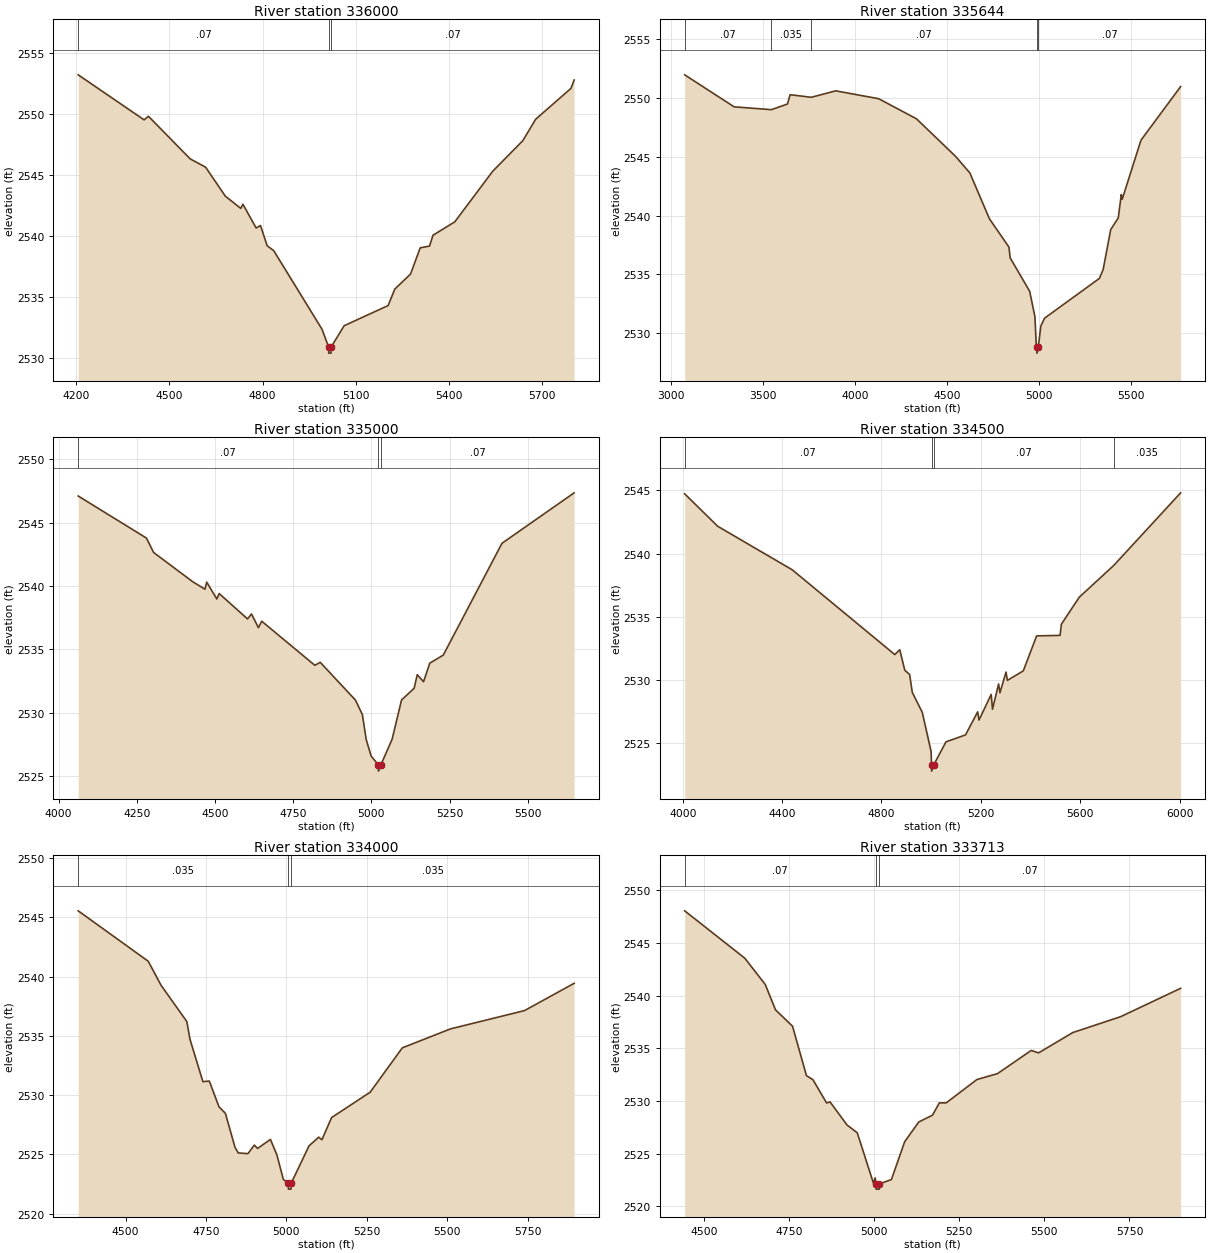
Type RM Length L Ch R = 1,336000,356,356,356
BEGIN DESCRIPTION:
Sweetwater Creek 670.0
END DESCRIPTION:
XS GIS Cut Line= 3
      1357605.02      6775138.02      1358177.42      6775687.99
      1358955.01      6775888.00
#Sta/Elev= 30
  4206.2 2553.18  4418.3 2549.50  4432.4 2549.79  4566.7 2546.31  4616.4 2545.63
  4679.9 2543.26  4729.6 2542.26  4736.5 2542.60  4779.0 2540.66  4793.1 2540.86
  4814.5 2539.21  4835.6 2538.81  4991.2 2532.38  5012.4 2530.93  5012.9 2530.43
  5020.2 2530.43  5020.7 2530.93  5062.4 2532.67  5204.0 2534.32  5225.3 2535.66
  5276.3 2536.90  5307.3 2539.04  5337.2 2539.18  5348.6 2540.07  5418.6 2541.16
  5540.8 2545.30  5637.7 2547.80  5679.0 2549.55  5792.6 2552.07  5802.9 2552.76
#Mann=3,-1,0
  4206.2    0.07       0  5012.4    0.07       0  5020.7    0.07       0
Bank Sta=5012.4,5020.7
Exp/Cntr=0.3,0.1

Type RM Length L Ch R = 1,335644,644,644,644
BEGIN DESCRIPTION:
Sweetwater Creek 669.0
END DESCRIPTION:
XS GIS Cut Line= 3
      1356554.99      6774687.99      1358004.33      6775958.08
      1358754.97      6776137.99
#Sta/Elev= 30
  3072.9 2551.96  3342.0 2549.24  3544.8 2549.00  3632.4 2549.48  3646.6 2550.27
  3761.7 2550.05  3895.2 2550.60  4128.7 2549.93  4334.6 2548.22  4547.2 2545.03
  4625.0 2543.62  4731.3 2539.73  4837.6 2537.32  4844.3 2536.41  4950.6 2533.56
  4979.0 2531.40  4986.6 2528.90  4989.1 2528.81  4989.6 2528.31  4997.4 2528.81
  5011.0 2530.61  5031.5 2531.28  5329.8 2534.66  5350.3 2535.41  5391.5 2538.81
  5432.6 2539.80  5449.1 2541.79  5454.2 2541.39  5556.0 2546.40  5771.9 2550.96
#Mann=5,-1,0
  3072.9    0.07       0  3544.8   0.035       0  3761.7    0.07       0
  4989.1    0.07       0  4997.4    0.07       0
Bank Sta=4989.1,4997.4
Exp/Cntr=0.3,0.1

Type RM Length L Ch R = 1,335000,500,500,500
BEGIN DESCRIPTION:
Sweetwater Creek 668.0
END DESCRIPTION:
XS GIS Cut Line= 3
      1357505.00      6775588.01      1357908.91      6776434.04
      1358554.96      6776488.00
#Sta/Elev= 30
  4062.5 2547.10  4280.8 2543.78  4303.5 2542.65  4428.2 2540.35  4467.8 2539.75
  4473.4 2540.31  4505.7 2538.98  4513.2 2539.41  4603.9 2537.41  4616.6 2537.80
  4638.7 2536.72  4649.3 2537.23  4819.2 2533.75  4836.3 2533.99  4949.0 2531.01
  4971.1 2529.87  4983.5 2527.89  4999.4 2526.59  5022.0 2525.91  5022.5 2525.41
  5030.4 2525.91  5066.3 2527.93  5096.4 2531.02  5136.6 2531.94  5146.6 2533.01
  5166.7 2532.46  5186.7 2533.92  5229.9 2534.56  5417.5 2543.37  5648.3 2547.35
#Mann=3,-1,0
  4062.5    0.07       0  5022.0    0.07       0  5030.4    0.07       0
Bank Sta=5022,5030.4
Exp/Cntr=0.3,0.1

Type RM Length L Ch R = 1,334500,500,500,500
BEGIN DESCRIPTION:
Sweetwater Creek 667.0
END DESCRIPTION:
XS GIS Cut Line= 3
      1357455.01      6775788.05      1357569.48      6776773.52
      1358504.99      6777138.00
#Sta/Elev= 30
  4007.9 2544.73  4140.8 2542.16  4440.7 2538.71  4853.5 2531.99  4873.6 2532.37
  4893.8 2530.75  4913.3 2530.41  4924.0 2528.99  4964.2 2527.41  4999.7 2524.31
  5001.4 2523.25  5001.9 2522.75  5010.5 2523.25  5059.6 2525.07  5138.2 2525.62
  5187.2 2527.45  5192.6 2526.80  5241.6 2528.83  5246.9 2527.66  5271.4 2529.66
  5276.8 2528.96  5301.3 2530.60  5306.7 2529.94  5370.8 2530.70  5424.5 2533.47
  5518.8 2533.51  5524.2 2534.40  5596.2 2536.54  5734.7 2539.05  6004.0 2544.81
#Mann=4,-1,0
  4007.9    0.07       0  5001.4    0.07       0  5010.5    0.07       0
  5734.7   0.035       0
Bank Sta=5001.4,5010.5
Exp/Cntr=0.3,0.1

Type RM Length L Ch R = 1,334000,287,287,287
BEGIN DESCRIPTION:
Sweetwater Creek 666.0
END DESCRIPTION:
XS GIS Cut Line= 3
      1356657.35      6777157.29      1357304.65      6777145.58
      1358199.34      6777142.13
#Sta/Elev= 30
  4352.6 2545.54  4570.3 2541.29  4610.3 2539.26  4690.3 2536.21  4700.3 2534.70
  4740.3 2531.14  4760.3 2531.19  4790.3 2529.02  4810.3 2528.47  4840.3 2525.59
  4850.3 2525.13  4880.3 2525.07  4900.3 2525.79  4910.3 2525.51  4950.3 2526.27
  4970.3 2524.97  4990.4 2522.90  5005.8 2522.58  5006.3 2522.08  5014.4 2522.08
  5014.9 2522.58  5070.4 2525.73  5100.4 2526.46  5110.4 2526.24  5140.4 2528.11
  5260.4 2530.25  5360.4 2533.99  5510.4 2535.59  5740.4 2537.13  5894.7 2539.43
#Mann=3,-1,0
  4352.6   0.035       0  5005.8   0.035       0  5014.9   0.035       0
Bank Sta=5005.8,5014.9
Exp/Cntr=0.3,0.1

Type RM Length L Ch R = 1,333713,713,713,713
BEGIN DESCRIPTION:
Sweetwater Creek 665.0
END DESCRIPTION:
XS GIS Cut Line= 3
      1356748.41      6777460.34      1357304.94      6777433.03
      1358200.00      6777336.06
#Sta/Elev= 30
  4442.8 2548.06  4619.6 2543.56  4679.7 2541.06  4709.7 2538.66  4759.8 2537.10
  4800.7 2532.41  4819.8 2532.02  4859.9 2529.81  4869.9 2529.92  4920.0 2527.72
  4950.0 2526.98  4997.5 2522.20  5002.7 2522.70  5004.9 2522.13  5005.4 2521.63
  5014.8 2521.63  5015.3 2522.13  5050.4 2522.54  5089.3 2526.13  5130.8 2528.01
  5171.1 2528.65  5191.2 2529.82  5211.3 2529.82  5301.8 2532.04  5362.2 2532.60
  5461.1 2534.80  5482.9 2534.57  5583.5 2536.50  5724.3 2538.01  5900.3 2540.70
#Mann=3,-1,0
  4442.8    0.07       0  5004.9    0.07       0  5015.3    0.07       0
Bank Sta=5004.9,5015.3
Exp/Cntr=0.3,0.1

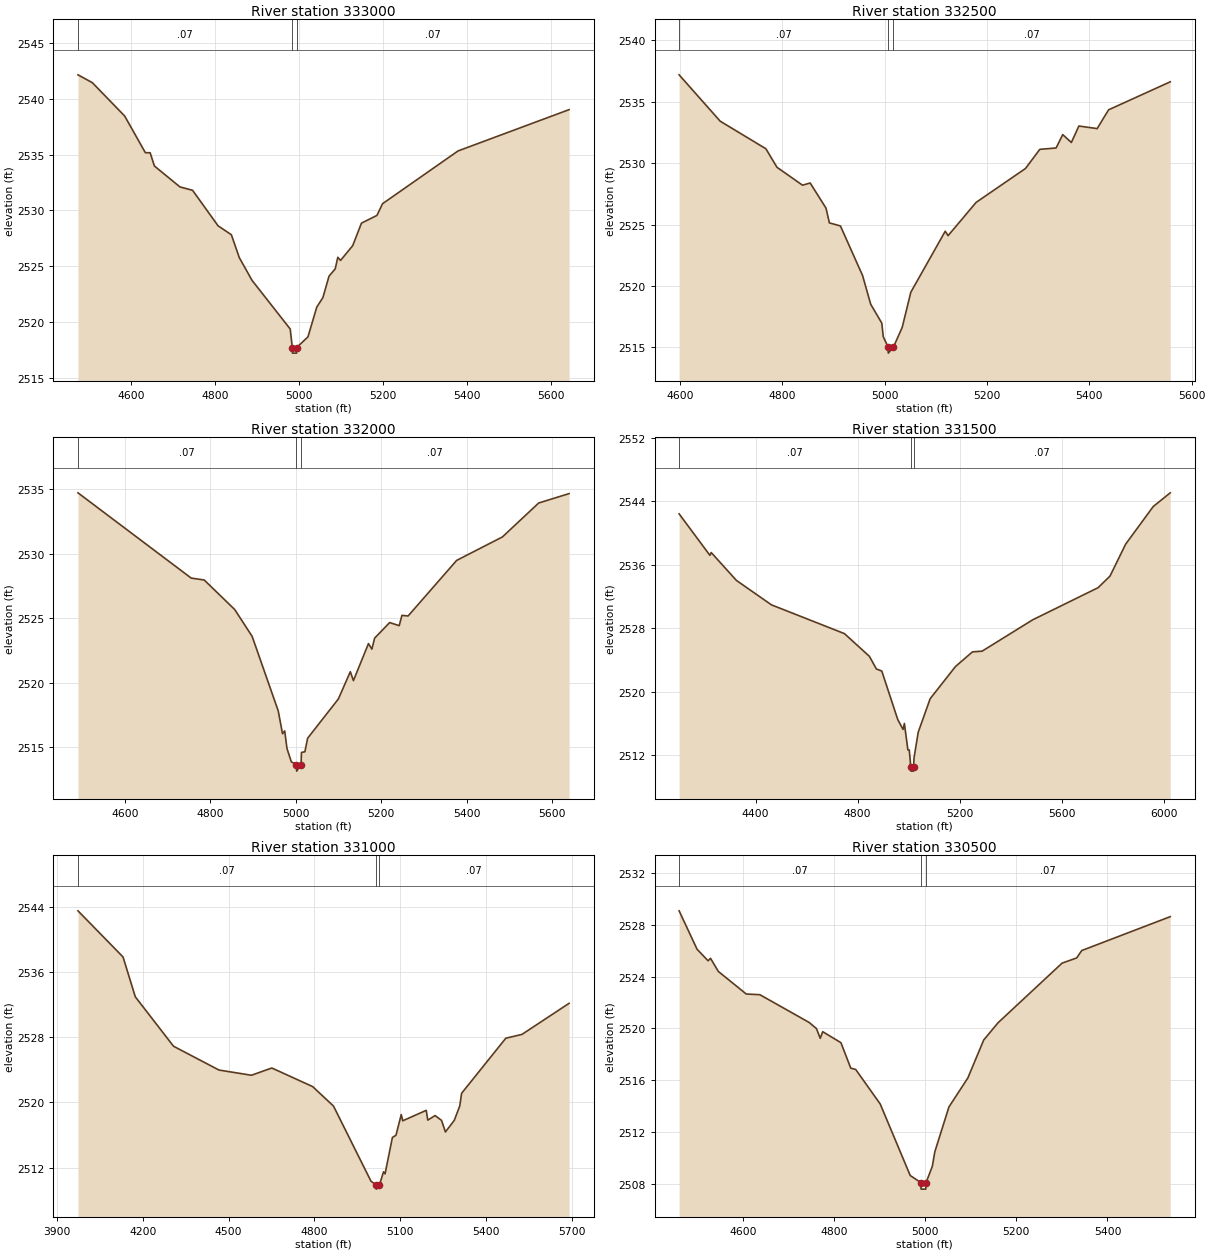
Type RM Length L Ch R = 1,333000,500,500,500
BEGIN DESCRIPTION:
Sweetwater Creek 664.0
END DESCRIPTION:
XS GIS Cut Line= 3
      1357204.96      6778038.01      1357725.83      6777957.90
      1358105.02      6777437.98
#Sta/Elev= 30
  4473.0 2542.14  4507.2 2541.44  4584.3 2538.45  4633.7 2535.16  4645.0 2535.16
  4655.2 2533.97  4715.9 2532.10  4746.2 2531.79  4806.9 2528.61  4838.6 2527.81
  4857.5 2525.76  4887.9 2523.72  4978.9 2519.36  4983.8 2517.70  4984.3 2517.20
  4993.8 2517.20  4994.3 2517.70  5021.2 2518.66  5042.1 2521.32  5056.8 2522.18
  5071.4 2524.10  5086.1 2524.75  5092.3 2525.79  5098.9 2525.51  5127.8 2526.83
  5148.7 2528.85  5185.5 2529.54  5198.9 2530.59  5378.9 2535.32  5643.5 2539.02
#Mann=3,-1,0
  4473.0    0.07       0  4983.8    0.07       0  4994.3    0.07       0
Bank Sta=4983.8,4994.3
Exp/Cntr=0.3,0.1

Type RM Length L Ch R = 1,332500,500,500,500
BEGIN DESCRIPTION:
Sweetwater Creek 663.0
END DESCRIPTION:
XS GIS Cut Line= 3
      1357354.99      6778238.00      1357704.99      6778435.95
      1358204.99      6778188.00
#Sta/Elev= 30
  4597.9 2537.20  4678.3 2533.42  4767.5 2531.18  4789.2 2529.67  4839.2 2528.21
  4854.1 2528.39  4885.1 2526.34  4891.7 2525.14  4913.3 2524.89  4956.6 2520.85
  4972.5 2518.51  4994.1 2516.98  4997.1 2515.86  5006.4 2515.03  5006.9 2514.53
  5017.0 2515.03  5034.1 2516.63  5050.9 2519.49  5118.2 2524.46  5123.8 2524.10
  5178.6 2526.81  5275.1 2529.57  5303.1 2531.13  5334.9 2531.24  5347.9 2532.33
  5364.8 2531.69  5379.5 2533.03  5415.2 2532.82  5437.6 2534.35  5558.1 2536.63
#Mann=3,-1,0
  4597.9    0.07       0  5006.4    0.07       0  5017.0    0.07       0
Bank Sta=5006.4,5017
Exp/Cntr=0.3,0.1

Type RM Length L Ch R = 1,332000,500,500,500
BEGIN DESCRIPTION:
Sweetwater Creek 662.0
END DESCRIPTION:
XS GIS Cut Line= 3
      1357305.01      6778988.00      1357804.99      6778887.87
      1358204.99      6778388.01
#Sta/Elev= 30
  4490.1 2534.74  4755.2 2528.13  4785.8 2527.98  4857.2 2525.69  4898.0 2523.61
  4959.2 2517.82  4969.1 2516.06  4974.2 2516.28  4979.6 2514.91  4989.8 2513.88
  5001.7 2513.66  5002.2 2513.16  5012.5 2513.66  5013.5 2514.61  5021.5 2514.66
  5027.9 2515.71  5100.0 2518.76  5127.9 2520.87  5135.2 2520.18  5170.4 2523.05
  5178.4 2522.62  5184.8 2523.47  5220.0 2524.68  5242.4 2524.44  5248.8 2525.24
  5263.2 2525.19  5376.9 2529.50  5484.1 2531.32  5569.0 2533.95  5640.2 2534.68
#Mann=3,-1,0
  4490.1    0.07       0  5001.7    0.07       0  5012.5    0.07       0
Bank Sta=5001.7,5012.5
Exp/Cntr=0.3,0.1

Type RM Length L Ch R = 1,331500,500,500,500
BEGIN DESCRIPTION:
Sweetwater Creek 661.0
END DESCRIPTION:
XS GIS Cut Line= 3
      1357055.02      6779088.00      1357916.13      6779347.97
      1358855.02      6778937.99
#Sta/Elev= 30
  4100.5 2542.41  4221.1 2537.19  4226.3 2537.54  4325.2 2534.02  4462.3 2530.95
  4748.1 2527.33  4845.9 2524.47  4873.5 2522.87  4894.4 2522.62  4957.0 2516.51
  4977.7 2515.26  4983.0 2516.01  4996.8 2512.68  5002.1 2512.68  5008.3 2510.51
  5008.8 2510.01  5018.7 2510.01  5019.2 2510.51  5020.6 2511.63  5037.2 2514.91
  5084.0 2519.13  5183.1 2523.18  5249.7 2525.03  5287.6 2525.12  5485.8 2529.07
  5741.7 2533.11  5788.5 2534.57  5849.9 2538.60  5957.8 2543.33  6024.5 2545.06
#Mann=3,-1,0
  4100.5    0.07       0  5008.3    0.07       0  5019.2    0.07       0
Bank Sta=5008.3,5019.2
Exp/Cntr=0.3,0.1

Type RM Length L Ch R = 1,331000,500,500,500
BEGIN DESCRIPTION:
Sweetwater Creek 660.0
END DESCRIPTION:
XS GIS Cut Line= 3
      1356905.00      6779588.00      1357904.91      6779818.31
      1358555.02      6779587.99
#Sta/Elev= 30
  3973.9 2543.49  4131.4 2537.83  4174.2 2532.95  4307.7 2526.89  4466.5 2523.97
  4579.9 2523.33  4651.2 2524.22  4793.9 2521.94  4866.7 2519.55  4997.5 2510.35
  5015.7 2509.87  5016.2 2509.37  5027.0 2509.87  5041.5 2511.49  5046.8 2511.24
  5072.4 2515.70  5085.0 2515.98  5103.3 2518.51  5108.6 2517.75  5190.7 2519.03
  5196.0 2517.83  5221.5 2518.39  5244.1 2517.80  5257.7 2516.38  5288.6 2517.80
  5307.8 2519.57  5314.2 2521.12  5468.6 2527.87  5525.1 2528.34  5689.7 2532.15
#Mann=3,-1,0
  3973.9    0.07       0  5015.7    0.07       0  5027.0    0.07       0
Bank Sta=5015.7,5027
Exp/Cntr=0.3,0.1

Type RM Length L Ch R = 1,330500,500,500,500
BEGIN DESCRIPTION:
Sweetwater Creek 659.0
END DESCRIPTION:
XS GIS Cut Line= 3
      1357105.00      6779988.00      1357606.54      6780186.52
      1358104.96      6780387.98
#Sta/Elev= 30
  4460.6 2529.06  4499.8 2526.11  4524.1 2525.21  4529.5 2525.40  4546.6 2524.39
  4607.9 2522.65  4637.6 2522.60  4745.8 2520.46  4761.7 2519.99  4770.1 2519.24
  4775.5 2519.75  4815.5 2518.90  4837.0 2516.94  4847.8 2516.84  4901.6 2514.18
  4967.4 2508.67  4990.8 2508.12  4991.3 2507.62  5001.6 2507.62  5002.1 2508.12
  5015.9 2509.38  5021.3 2510.49  5052.3 2513.95  5093.7 2516.18  5128.6 2519.11
  5160.1 2520.44  5300.4 2525.03  5332.4 2525.43  5343.5 2526.00  5537.6 2528.61
#Mann=3,-1,0
  4460.6    0.07       0  4990.8    0.07       0  5002.1    0.07       0
Bank Sta=4990.8,5002.1
Exp/Cntr=0.3,0.1