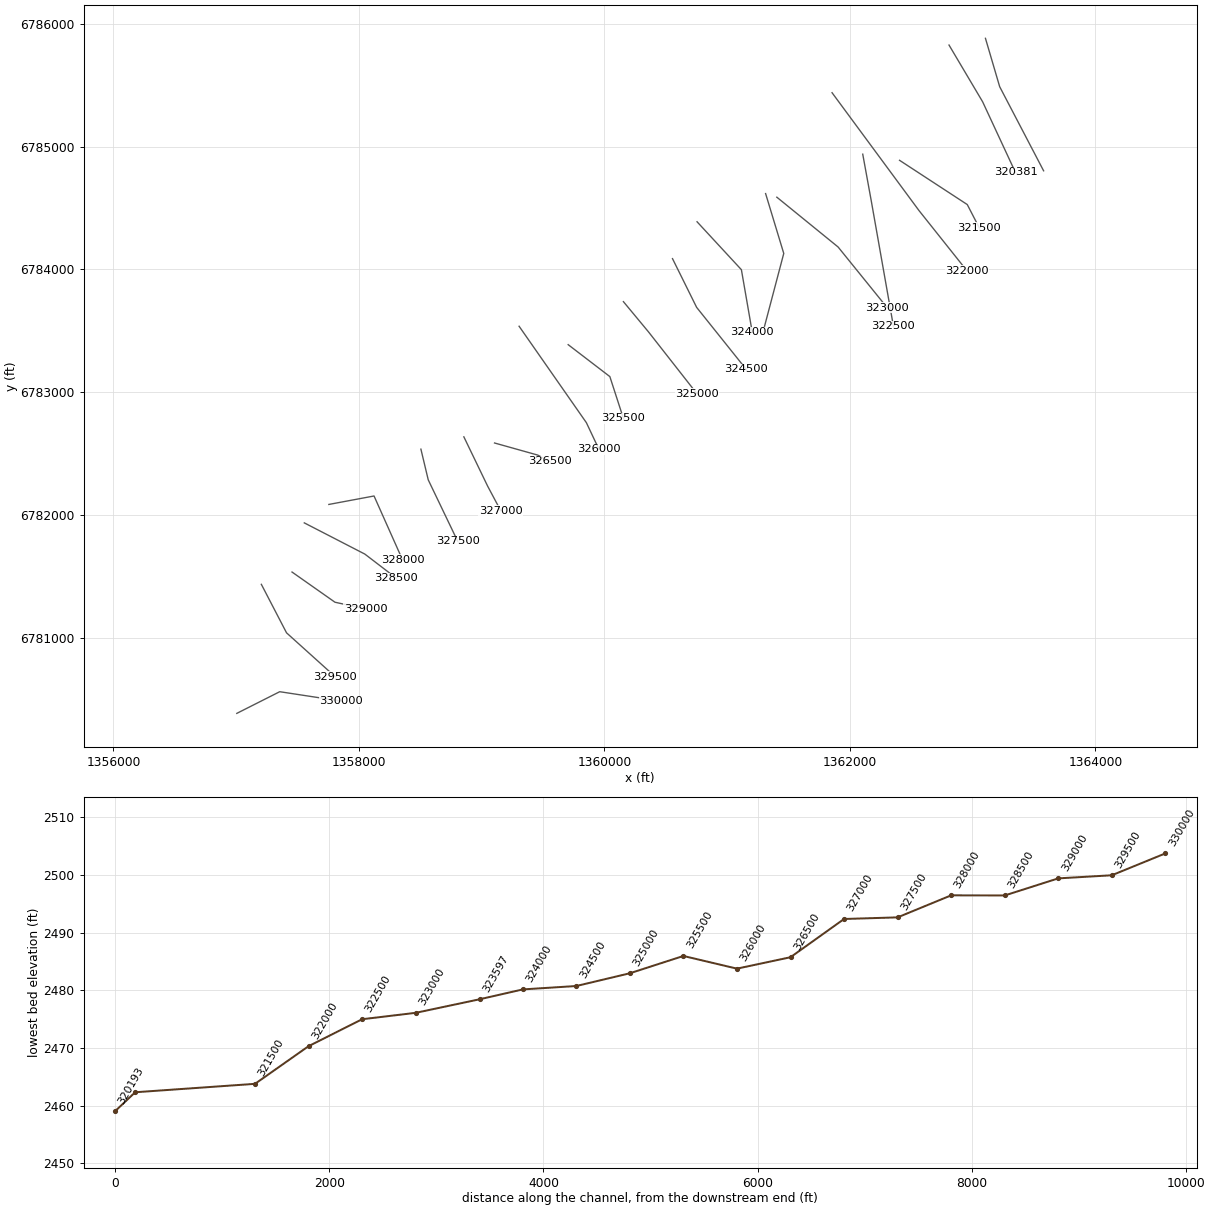
HEC-RAS study Sweetwater Creek.prj: Sweetwater Creek Base Level Engineering

--- Sweetwater Creek.g01 (geometry) --- (continued)

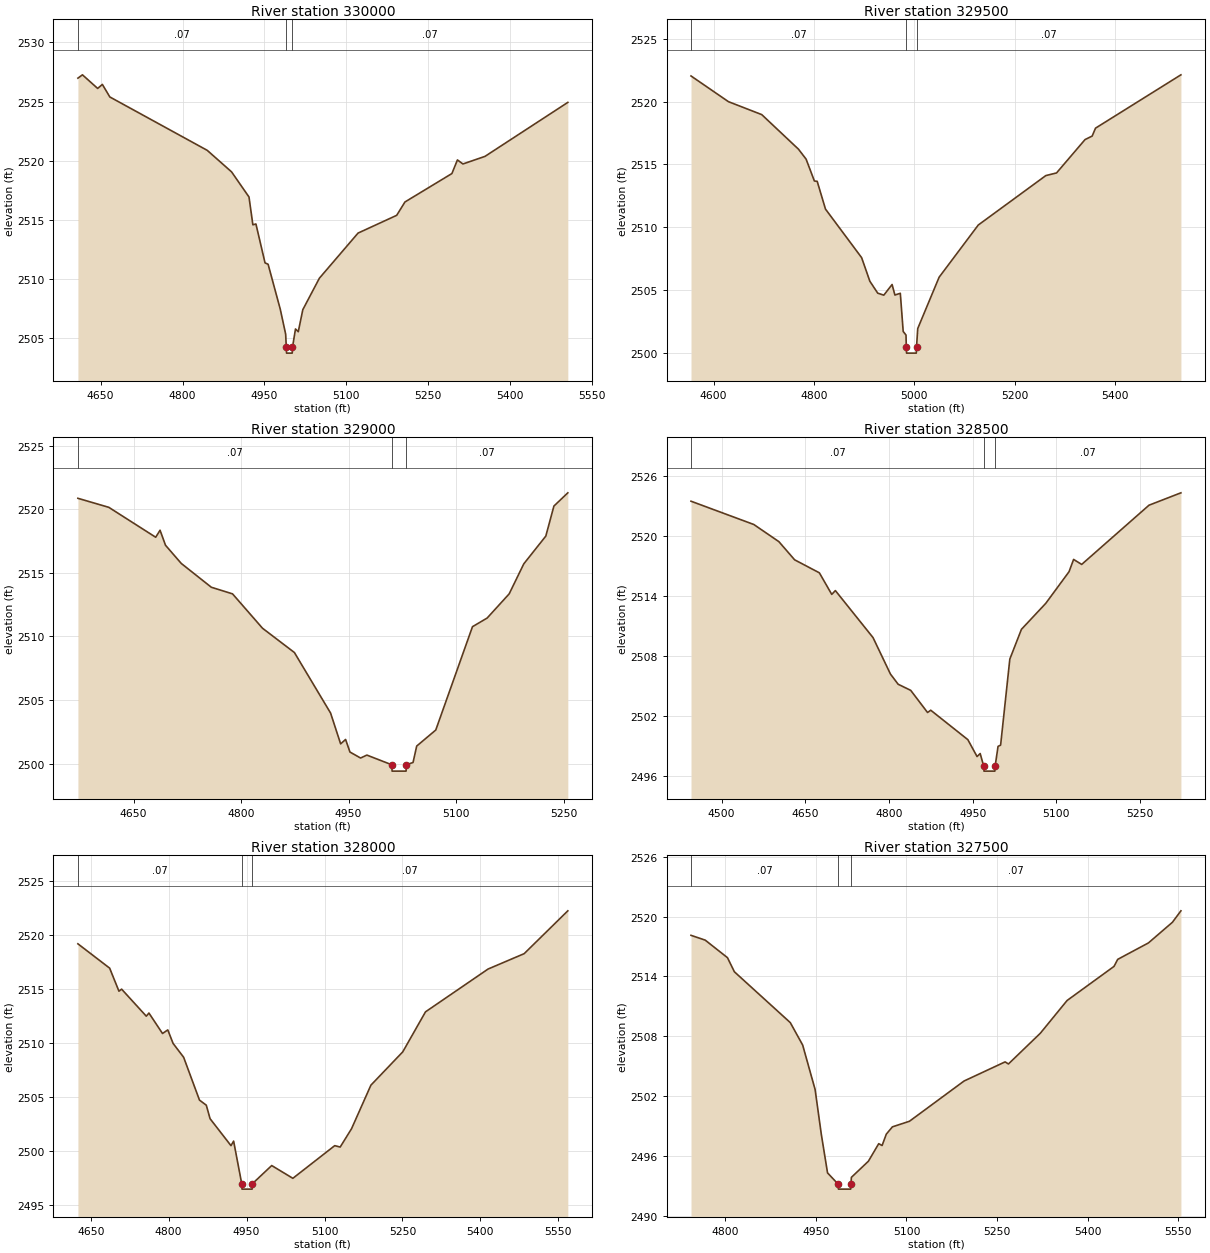
Type RM Length L Ch R = 1,330000,500,500,500
BEGIN DESCRIPTION:
Sweetwater Creek 658.0
END DESCRIPTION:
XS GIS Cut Line= 3
      1357005.03      6780388.01      1357354.80      6780564.33
      1357855.01      6780488.00
#Sta/Elev= 30
  4608.3 2526.98  4616.6 2527.26  4644.5 2526.11  4653.1 2526.45  4666.8 2525.39
  4845.3 2520.88  4889.9 2519.06  4921.8 2516.94  4928.9 2514.59  4934.5 2514.66
  4951.2 2511.37  4956.8 2511.26  4979.1 2507.46  4989.0 2505.35  4990.1 2504.25
  4990.6 2503.75  5001.0 2503.75  5001.5 2504.25  5007.0 2505.79  5012.1 2505.56
  5020.4 2507.42  5050.8 2510.08  5121.6 2513.89  5192.4 2515.39  5207.6 2516.52
  5293.6 2518.92  5303.7 2520.07  5313.8 2519.73  5354.2 2520.37  5506.0 2524.93
#Mann=3,-1,0
  4608.3    0.07       0  4990.1    0.07       0  5001.5    0.07       0
Bank Sta=4990.1,5001.5
Exp/Cntr=0.3,0.1

Type RM Length L Ch R = 1,329500,500,500,500
BEGIN DESCRIPTION:
Sweetwater Creek 657.0
END DESCRIPTION:
XS GIS Cut Line= 3
      1357204.99      6781438.01      1357410.28      6781043.30
      1357805.01      6780687.99
#Sta/Elev= 30
  4555.1 2522.05  4629.7 2520.00  4696.0 2518.97  4769.3 2516.21  4784.4 2515.42
  4800.9 2513.68  4806.5 2513.65  4823.0 2511.44  4895.0 2507.57  4911.4 2505.69
  4927.1 2504.74  4939.2 2504.58  4955.7 2505.43  4961.3 2504.59  4972.1 2504.73
  4977.8 2501.69  4983.4 2501.40  4984.0 2500.46  4984.5 2499.96  5003.9 2499.96
  5004.4 2500.46  5006.8 2501.92  5049.4 2506.01  5127.4 2510.17  5262.0 2514.11
  5283.3 2514.32  5340.1 2516.98  5354.3 2517.26  5361.0 2517.89  5531.1 2522.14
#Mann=3,-1,0
  4555.1    0.07       0  4984.0    0.07       0  5004.4    0.07       0
Bank Sta=4984,5004.4
Exp/Cntr=0.3,0.1

Type RM Length L Ch R = 1,329000,500,500,500
BEGIN DESCRIPTION:
Sweetwater Creek 656.0
END DESCRIPTION:
XS GIS Cut Line= 3
      1357455.01      6781538.00      1357805.00      6781292.34
      1358054.97      6781238.01
#Sta/Elev= 30
  4572.4 2520.86  4615.5 2520.15  4680.9 2517.80  4687.0 2518.35  4694.6 2517.17
  4716.6 2515.74  4758.5 2513.87  4788.1 2513.35  4829.9 2510.65  4874.4 2508.74
  4924.9 2503.98  4938.9 2501.56  4945.8 2501.91  4951.9 2500.92  4966.7 2500.45
  4975.5 2500.68  5010.2 2499.92  5010.7 2499.42  5030.2 2499.42  5030.7 2499.92
  5039.9 2500.10  5045.0 2501.39  5071.6 2502.65  5122.8 2510.77  5143.3 2511.45
  5174.0 2513.35  5194.4 2515.71  5225.1 2517.89  5236.4 2520.25  5255.8 2521.29
#Mann=3,-1,0
  4572.4    0.07       0  5010.2    0.07       0  5030.7    0.07       0
Bank Sta=5010.2,5030.7
Exp/Cntr=0.3,0.1

Type RM Length L Ch R = 1,328500,500,500,500
BEGIN DESCRIPTION:
Sweetwater Creek 655.0
END DESCRIPTION:
XS GIS Cut Line= 3
      1357554.96      6781938.02      1358048.22      6781684.05
      1358305.03      6781487.98
#Sta/Elev= 30
  4445.2 2523.49  4557.7 2521.16  4602.7 2519.44  4630.9 2517.62  4675.2 2516.32
  4697.4 2514.16  4703.9 2514.54  4771.4 2509.83  4802.6 2506.18  4816.4 2505.16
  4838.9 2504.55  4869.1 2502.33  4874.8 2502.56  4941.3 2499.61  4957.8 2497.92
  4963.4 2498.22  4969.7 2496.96  4970.2 2496.46  4989.7 2496.46  4990.2 2496.96
  4995.4 2498.94  5000.0 2499.06  5016.5 2507.68  5037.3 2510.66  5080.9 2513.26
  5122.6 2516.43  5130.8 2517.66  5145.3 2517.16  5265.9 2523.09  5323.1 2524.33
#Mann=3,-1,0
  4445.2    0.07       0  4969.7    0.07       0  4990.2    0.07       0
Bank Sta=4969.7,4990.2
Exp/Cntr=0.3,0.1

Type RM Length L Ch R = 1,328000,500,500,500
BEGIN DESCRIPTION:
Sweetwater Creek 654.0
END DESCRIPTION:
XS GIS Cut Line= 3
      1357754.97      6782087.99      1358123.19      6782156.83
      1358355.01      6781637.97
#Sta/Elev= 30
  4625.4 2519.16  4686.5 2516.91  4704.4 2514.78  4709.5 2514.97  4757.0 2512.47
  4762.1 2512.76  4788.2 2510.87  4798.4 2511.20  4808.6 2509.95  4828.9 2508.67
  4859.4 2504.71  4872.5 2504.24  4879.8 2502.99  4920.0 2500.50  4925.1 2500.92
  4940.7 2496.98  4941.2 2496.48  4960.7 2496.48  4961.2 2496.98  4998.4 2498.66
  5039.1 2497.48  5119.7 2500.50  5130.2 2500.37  5152.1 2502.07  5189.3 2506.09
  5250.6 2509.17  5294.4 2512.87  5414.9 2516.83  5484.3 2518.25  5568.3 2522.21
#Mann=3,-1,0
  4625.4    0.07       0  4940.7    0.07       0  4961.2    0.07       0
Bank Sta=4940.7,4961.2
Exp/Cntr=0.3,0.1

Type RM Length L Ch R = 1,327500,500,500,500
BEGIN DESCRIPTION:
Sweetwater Creek 653.0
END DESCRIPTION:
XS GIS Cut Line= 3
      1358505.01      6782537.96      1358564.84      6782288.02
      1358805.00      6781788.00
#Sta/Elev= 30
  4743.0 2518.13  4766.5 2517.65  4803.4 2515.89  4814.9 2514.47  4907.5 2509.37
  4928.0 2507.12  4948.6 2502.66  4958.9 2498.16  4969.2 2494.29  4986.8 2493.16
  4987.3 2492.66  5007.6 2492.66  5008.1 2493.16  5008.7 2493.84  5036.9 2495.46
  5054.0 2497.22  5059.6 2497.04  5066.6 2498.18  5076.7 2498.91  5104.9 2499.47
  5195.4 2503.51  5263.4 2505.43  5268.9 2505.22  5321.7 2508.30  5366.1 2511.59
  5443.8 2515.01  5450.0 2515.72  5500.9 2517.37  5540.6 2519.44  5554.7 2520.59
#Mann=3,-1,0
  4743.0    0.07       0  4986.8    0.07       0  5008.1    0.07       0
Bank Sta=4986.8,5008.1
Exp/Cntr=0.3,0.1

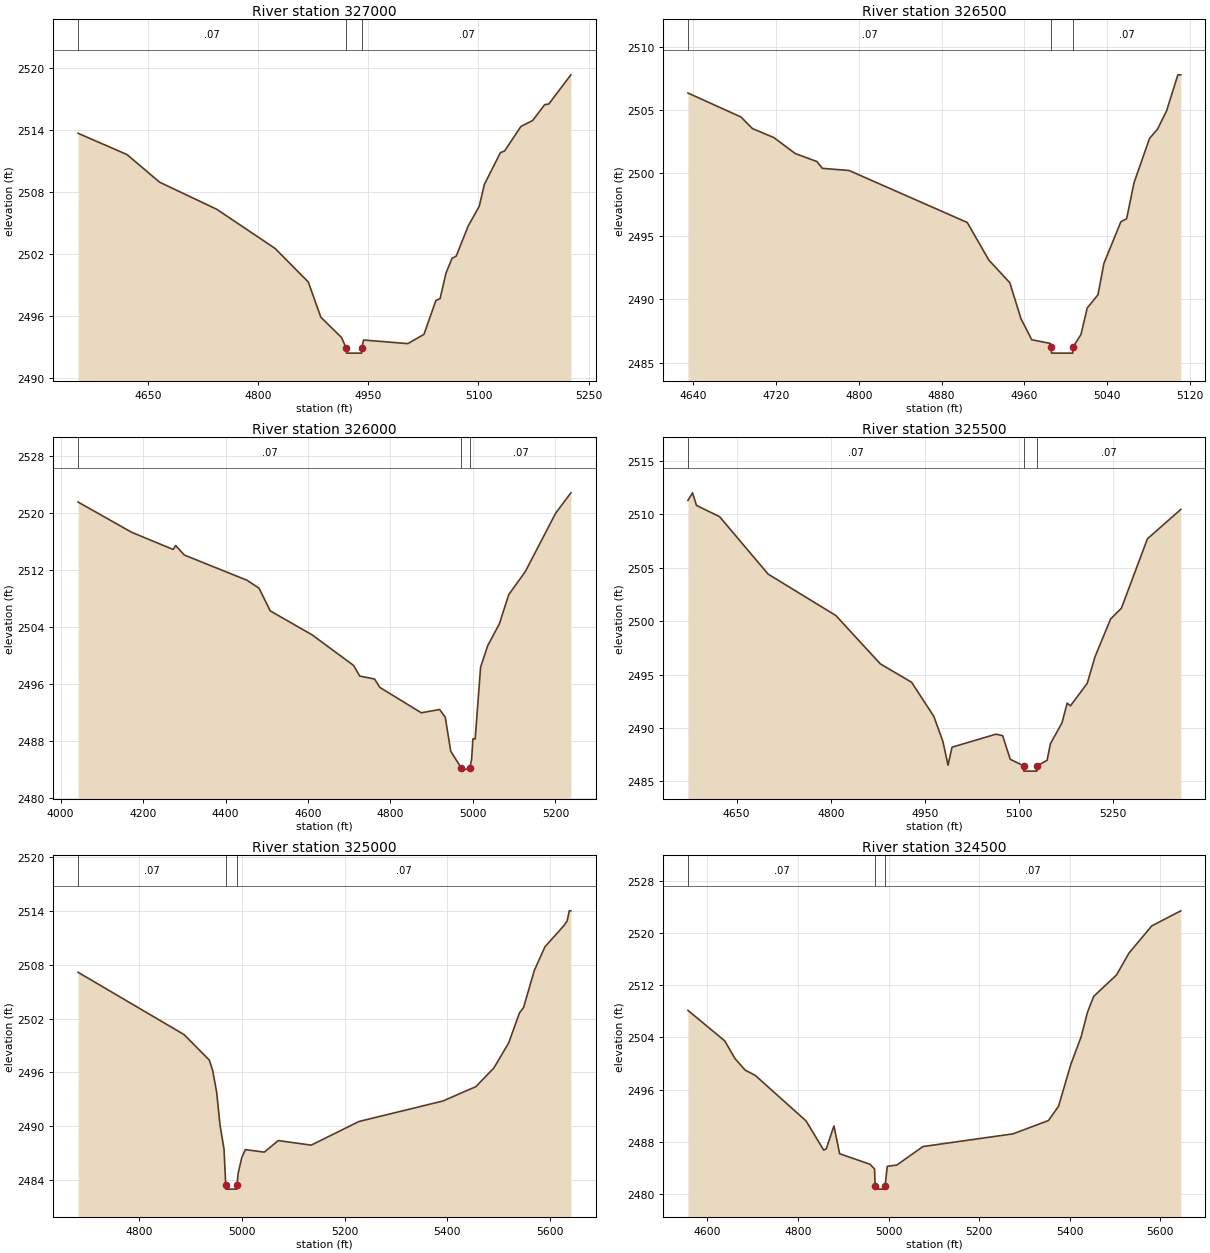
Type RM Length L Ch R = 1,327000,500,500,500
BEGIN DESCRIPTION:
Sweetwater Creek 652.0
END DESCRIPTION:
XS GIS Cut Line= 3
      1358855.00      6782638.00      1359048.64      6782237.23
      1359154.98      6782038.03
#Sta/Elev= 30
  4554.9 2513.67  4621.5 2511.61  4666.0 2508.93  4743.7 2506.31  4823.1 2502.52
  4868.3 2499.27  4885.4 2495.86  4913.5 2493.90  4919.9 2492.88  4920.4 2492.38
  4940.8 2492.38  4941.3 2492.88  4943.6 2493.65  5003.8 2493.30  5025.8 2494.20
  5042.1 2497.49  5047.7 2497.65  5055.8 2500.13  5064.0 2501.56  5069.7 2501.77
  5086.0 2504.69  5101.1 2506.61  5107.9 2508.70  5129.9 2511.80  5135.6 2511.96
  5157.8 2514.33  5173.8 2514.91  5190.1 2516.44  5195.7 2516.50  5225.8 2519.33
#Mann=3,-1,0
  4554.9    0.07       0  4919.9    0.07       0  4941.3    0.07       0
Bank Sta=4919.9,4941.3
Exp/Cntr=0.3,0.1

Type RM Length L Ch R = 1,326500,500,500,500
BEGIN DESCRIPTION:
Sweetwater Creek 651.0
END DESCRIPTION:
XS GIS Cut Line= 3
      1359105.04      6782587.99      1359456.66      6782489.71
      1359555.00      6782438.00
#Sta/Elev= 30
  4634.9 2506.36  4686.1 2504.46  4697.2 2503.54  4717.9 2502.83  4738.7 2501.56
  4759.5 2500.93  4764.8 2500.39  4790.6 2500.22  4904.8 2496.10  4925.6 2493.13
  4945.9 2491.33  4956.7 2488.48  4967.1 2486.81  4985.2 2486.52  4985.8 2486.25
  4986.3 2485.75  5006.7 2485.75  5007.2 2486.25  5014.7 2487.23  5020.7 2489.33
  5031.1 2490.37  5036.8 2492.85  5053.2 2496.16  5058.8 2496.40  5065.9 2499.24
  5080.9 2502.76  5088.5 2503.48  5097.3 2504.93  5108.3 2507.80  5111.1 2507.80
#Mann=3,-1,0
  4634.9    0.07       0  4985.8    0.07       0  5007.2    0.07       0
Bank Sta=4985.8,5007.2
Exp/Cntr=0.3,0.1

Type RM Length L Ch R = 1,326000,500,500,500
BEGIN DESCRIPTION:
Sweetwater Creek 650.0
END DESCRIPTION:
XS GIS Cut Line= 3
      1359305.02      6783537.97      1359853.51      6782752.89
      1359954.98      6782538.04
#Sta/Elev= 30
  4042.3 2521.50  4171.8 2517.27  4273.0 2514.85  4279.1 2515.40  4300.0 2514.07
  4451.8 2510.54  4481.4 2509.41  4508.4 2506.24  4609.6 2502.89  4710.8 2498.58
  4725.4 2497.10  4761.4 2496.69  4774.2 2495.51  4874.8 2491.95  4919.3 2492.41
  4932.8 2491.34  4946.3 2486.54  4971.2 2484.27  4971.7 2483.77  4992.8 2484.27
  4996.9 2485.46  4999.9 2488.29  5005.5 2488.29  5018.6 2498.34  5035.8 2501.35
  5064.1 2504.42  5086.9 2508.52  5126.9 2511.73  5200.7 2519.94  5237.6 2522.79
#Mann=3,-1,0
  4042.3    0.07       0  4971.2    0.07       0  4992.8    0.07       0
Bank Sta=4971.2,4992.8
Exp/Cntr=0.3,0.1

Type RM Length L Ch R = 1,325500,500,500,500
BEGIN DESCRIPTION:
Sweetwater Creek 649.0
END DESCRIPTION:
XS GIS Cut Line= 3
      1359705.00      6783388.00      1360044.55      6783128.27
      1360154.99      6782788.04
#Sta/Elev= 30
  4572.5 2511.31  4579.8 2512.02  4586.1 2510.84  4622.9 2509.79  4700.3 2504.41
  4808.3 2500.53  4879.0 2496.01  4928.8 2494.29  4964.2 2491.10  4978.7 2488.75
  4986.9 2486.53  4993.2 2488.21  5063.4 2489.43  5073.9 2489.29  5086.0 2487.08
  5107.2 2486.47  5107.7 2485.97  5128.4 2485.97  5128.9 2486.47  5144.7 2486.98
  5150.0 2488.53  5168.5 2490.50  5176.7 2492.34  5181.9 2492.08  5208.6 2494.18
  5221.1 2496.68  5245.9 2500.21  5263.1 2501.22  5304.5 2507.71  5357.7 2510.47
#Mann=3,-1,0
  4572.5    0.07       0  5107.2    0.07       0  5128.9    0.07       0
Bank Sta=5107.2,5128.9
Exp/Cntr=0.3,0.1

Type RM Length L Ch R = 1,325000,500,500,500
BEGIN DESCRIPTION:
Sweetwater Creek 648.0
END DESCRIPTION:
XS GIS Cut Line= 3
      1360155.02      6783737.98      1360359.21      6783492.25
      1360754.98      6782988.02
#Sta/Elev= 30
  4680.5 2507.18  4886.9 2500.23  4936.3 2497.38  4942.8 2496.23  4950.7 2493.76
  4957.2 2490.12  4965.0 2487.42  4968.3 2483.47  4968.8 2482.97  4989.9 2482.97
  4990.4 2483.47  4992.5 2484.73  4999.5 2486.48  5006.5 2487.38  5043.5 2487.10
  5070.7 2488.39  5134.9 2487.88  5227.9 2490.52  5391.6 2492.81  5455.7 2494.41
  5491.0 2496.50  5519.9 2499.31  5540.7 2502.63  5548.8 2503.25  5569.6 2507.36
  5590.4 2510.02  5627.4 2512.39  5633.8 2512.92  5637.8 2514.04  5641.0 2514.04
#Mann=3,-1,0
  4680.5    0.07       0  4968.3    0.07       0  4990.4    0.07       0
Bank Sta=4968.3,4990.4
Exp/Cntr=0.3,0.1

Type RM Length L Ch R = 1,324500,500,500,500
BEGIN DESCRIPTION:
Sweetwater Creek 647.0
END DESCRIPTION:
XS GIS Cut Line= 3
      1360555.01      6784087.97      1360751.69      6783691.36
      1361155.00      6783188.00
#Sta/Elev= 30
  4557.3 2508.13  4638.5 2503.46  4660.9 2500.77  4683.4 2498.99  4705.8 2498.18
  4817.9 2491.21  4857.1 2486.72  4862.7 2486.95  4879.5 2490.44  4892.1 2486.18
  4959.1 2484.57  4969.2 2483.84  4970.3 2481.26  4970.8 2480.76  4992.0 2480.76
  4992.5 2481.26  4997.2 2484.25  5018.4 2484.45  5076.0 2487.28  5274.5 2489.22
  5352.9 2491.26  5375.3 2493.46  5402.5 2499.89  5424.9 2504.05  5439.3 2507.88
  5452.8 2510.27  5503.4 2513.57  5530.6 2516.89  5580.9 2521.06  5645.0 2523.37
#Mann=3,-1,0
  4557.3    0.07       0  4970.3    0.07       0  4992.5    0.07       0
Bank Sta=4970.3,4992.5
Exp/Cntr=0.3,0.1

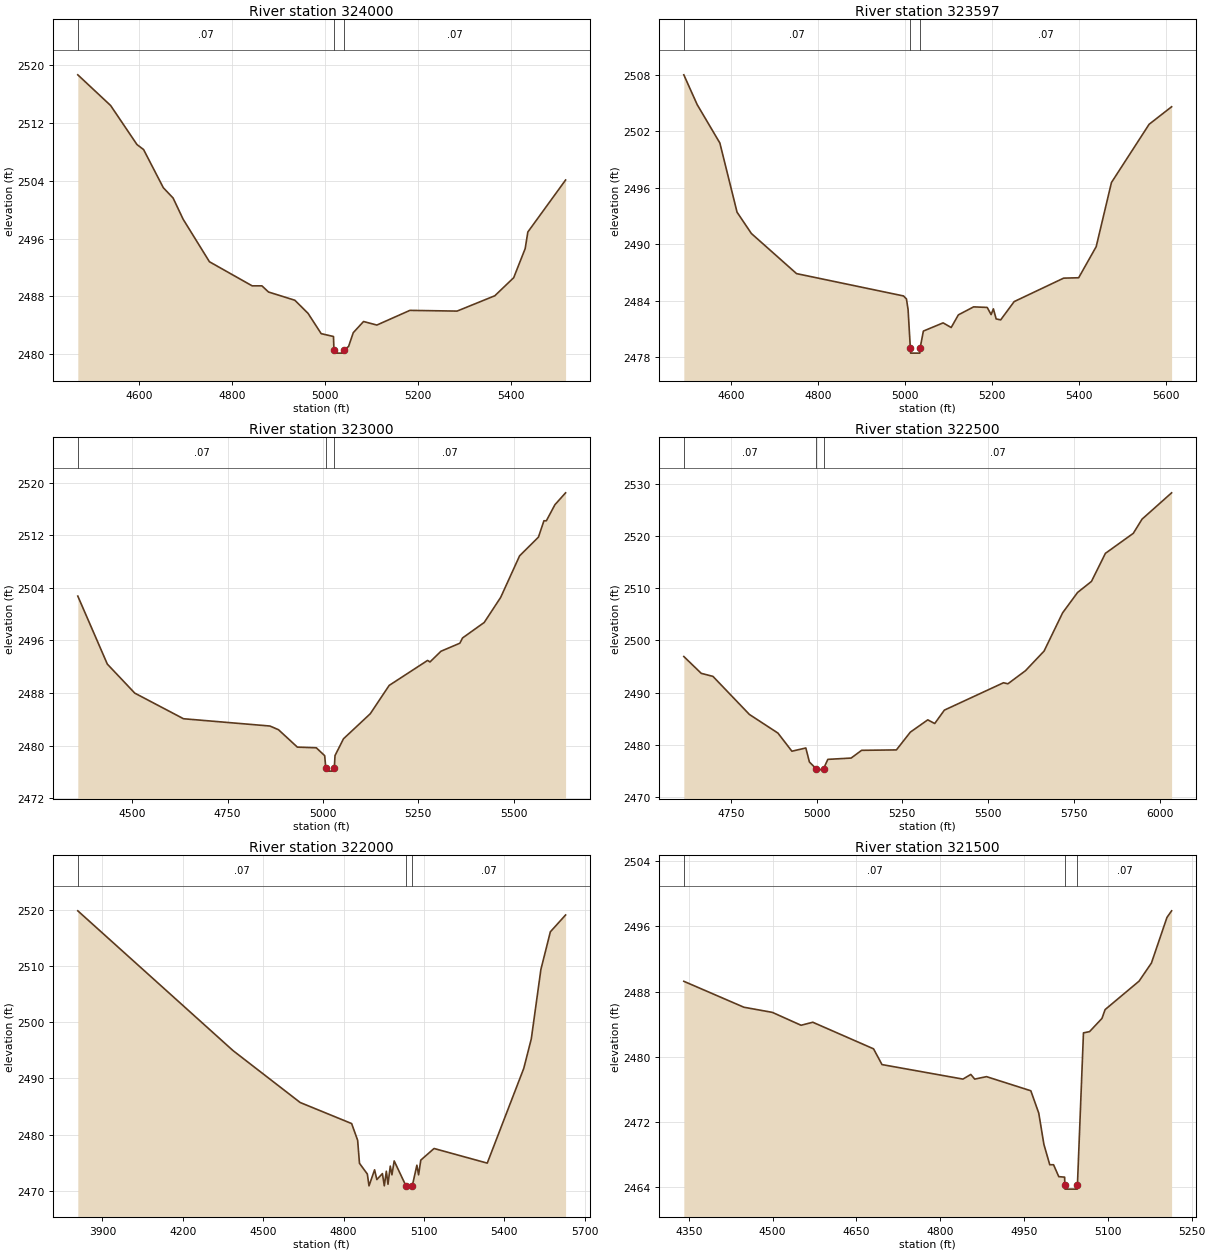
Type RM Length L Ch R = 1,324000,403,403,403
BEGIN DESCRIPTION:
Sweetwater Creek 646.0
END DESCRIPTION:
XS GIS Cut Line= 3
      1360754.99      6784388.01      1361116.32      6783997.96
      1361205.00      6783488.01
#Sta/Elev= 30
  4468.3 2518.64  4538.9 2514.40  4595.6 2509.00  4609.8 2508.31  4652.3 2503.03
  4673.3 2501.61  4694.8 2498.69  4751.5 2492.80  4843.4 2489.47  4864.4 2489.47
  4878.5 2488.62  4935.2 2487.48  4963.6 2485.67  4991.9 2482.86  5018.3 2482.47
  5019.3 2480.67  5019.8 2480.17  5041.0 2480.17  5041.5 2480.67  5050.7 2481.08
  5060.9 2483.00  5083.0 2484.54  5111.6 2484.05  5182.7 2486.08  5284.2 2485.98
  5365.4 2488.10  5406.0 2490.60  5430.7 2494.62  5436.4 2496.91  5517.6 2504.10
#Mann=3,-1,0
  4468.3    0.07       0  5019.3    0.07       0  5041.5    0.07       0
Bank Sta=5019.3,5041.5
Exp/Cntr=0.3,0.1

Type RM Length L Ch R = 1,323597,597,597,597
BEGIN DESCRIPTION:
Sweetwater Creek 645.0
END DESCRIPTION:
XS GIS Cut Line= 3
      1361313.56      6784617.34      1361461.47      6784130.31
      1361305.01      6783538.02
#Sta/Elev= 30
  4491.0 2508.00  4521.7 2504.84  4573.9 2500.76  4613.4 2493.42  4646.3 2491.16
  4750.2 2486.90  4996.1 2484.53  5002.9 2484.21  5006.7 2483.07  5011.9 2478.96
  5012.4 2478.46  5033.7 2478.46  5034.2 2478.96  5041.8 2480.80  5087.2 2481.67
  5105.8 2481.18  5122.3 2482.52  5157.4 2483.37  5188.6 2483.31  5197.6 2482.55
  5202.8 2483.16  5209.2 2482.09  5219.6 2481.99  5250.6 2483.93  5364.4 2486.42
  5398.9 2486.46  5439.2 2489.76  5474.3 2496.57  5560.9 2502.75  5612.6 2504.61
#Mann=3,-1,0
  4491.0    0.07       0  5011.9    0.07       0  5034.2    0.07       0
Bank Sta=5011.9,5034.2
Exp/Cntr=0.3,0.1

Type RM Length L Ch R = 1,323000,500,500,500
BEGIN DESCRIPTION:
Sweetwater Creek 644.0
END DESCRIPTION:
XS GIS Cut Line= 3
      1361405.02      6784587.98      1361904.27      6784182.61
      1362305.02      6783687.98
#Sta/Elev= 30
  4356.9 2502.74  4434.4 2492.39  4506.3 2487.98  4634.2 2484.08  4861.1 2482.97
  4883.4 2482.41  4933.0 2479.76  4982.6 2479.66  5004.6 2478.46  5007.5 2476.61
  5008.0 2476.11  5029.4 2476.11  5029.9 2476.61  5031.7 2478.47  5053.9 2481.03
  5124.2 2484.84  5173.8 2489.15  5274.5 2492.95  5280.9 2492.72  5309.7 2494.35
  5359.2 2495.57  5366.3 2496.37  5423.2 2498.73  5466.3 2502.54  5515.9 2508.86
  5565.4 2511.71  5579.8 2514.20  5586.2 2514.20  5608.6 2516.64  5636.6 2518.45
#Mann=3,-1,0
  4356.9    0.07       0  5007.5    0.07       0  5029.9    0.07       0
Bank Sta=5007.5,5029.9
Exp/Cntr=0.3,0.1

Type RM Length L Ch R = 1,322500,500,500,500
BEGIN DESCRIPTION:
Sweetwater Creek 643.0
END DESCRIPTION:
XS GIS Cut Line= 3
      1362105.01      6784937.95      1362174.57      6784557.36
      1362355.00      6783538.00
#Sta/Elev= 30
  4613.1 2496.93  4663.9 2493.71  4698.0 2493.13  4804.4 2485.84  4887.5 2482.28
  4928.2 2478.81  4968.8 2479.43  4979.3 2476.74  4998.3 2475.50  4998.8 2475.00
  5020.7 2475.50  5033.0 2477.25  5100.9 2477.50  5131.4 2478.98  5232.9 2479.06
  5273.5 2482.46  5324.3 2484.81  5344.6 2484.11  5372.7 2486.67  5545.1 2491.91
  5557.9 2491.71  5609.3 2494.22  5663.4 2497.97  5717.5 2505.29  5761.0 2509.18
  5801.6 2511.30  5842.2 2516.67  5923.5 2520.50  5949.0 2523.21  6035.2 2528.25
#Mann=3,-1,0
  4613.1    0.07       0  4998.3    0.07       0  5020.7    0.07       0
Bank Sta=4998.3,5020.7
Exp/Cntr=0.3,0.1

Type RM Length L Ch R = 1,322000,500,500,500
BEGIN DESCRIPTION:
Sweetwater Creek 642.0
END DESCRIPTION:
XS GIS Cut Line= 3
      1361855.01      6785437.99      1362563.14      6784479.38
      1362955.00      6783988.00
#Sta/Elev= 30
  3808.2 2519.78  4387.6 2494.94  4638.1 2485.72  4830.1 2481.98  4852.5 2479.01
  4859.4 2474.92  4888.7 2473.01  4894.9 2470.91  4915.7 2473.76  4924.2 2472.03
  4945.0 2473.09  4952.0 2470.92  4959.6 2473.51  4965.8 2471.19  4974.3 2474.42
  4980.5 2472.87  4988.9 2475.34  5033.6 2470.83  5034.1 2470.33  5056.1 2470.83
  5073.6 2474.58  5080.0 2472.87  5088.1 2475.48  5137.7 2477.55  5336.2 2474.95
  5472.4 2491.78  5500.6 2497.04  5536.4 2509.37  5571.7 2516.05  5628.5 2519.04
#Mann=3,-1,0
  3808.2    0.07       0  5033.6    0.07       0  5056.1    0.07       0
Bank Sta=5033.6,5056.1
Exp/Cntr=0.3,0.1

Type RM Length L Ch R = 1,321500,1119,1119,1119
BEGIN DESCRIPTION:
Sweetwater Creek 641.0
END DESCRIPTION:
XS GIS Cut Line= 3
      1362404.96      6784888.03      1362956.70      6784528.03
      1363055.02      6784337.96
#Sta/Elev= 30
  4341.2 2489.28  4448.7 2486.10  4499.6 2485.47  4551.0 2483.89  4572.0 2484.26
  4680.7 2481.00  4695.8 2479.07  4840.6 2477.29  4854.7 2477.86  4861.7 2477.29
  4882.8 2477.59  4962.1 2475.86  4976.3 2473.12  4985.5 2469.29  4996.0 2466.79
  5002.8 2466.79  5012.1 2465.33  5022.6 2465.27  5022.9 2464.30  5023.4 2463.80
  5045.0 2463.80  5045.5 2464.30  5056.3 2482.96  5067.2 2483.11  5089.4 2484.73
  5095.0 2485.81  5155.8 2489.30  5177.9 2491.52  5205.7 2497.11  5214.0 2497.92
#Mann=3,-1,0
  4341.2    0.07       0  5022.9    0.07       0  5045.5    0.07       0
Bank Sta=5022.9,5045.5
Exp/Cntr=0.3,0.1

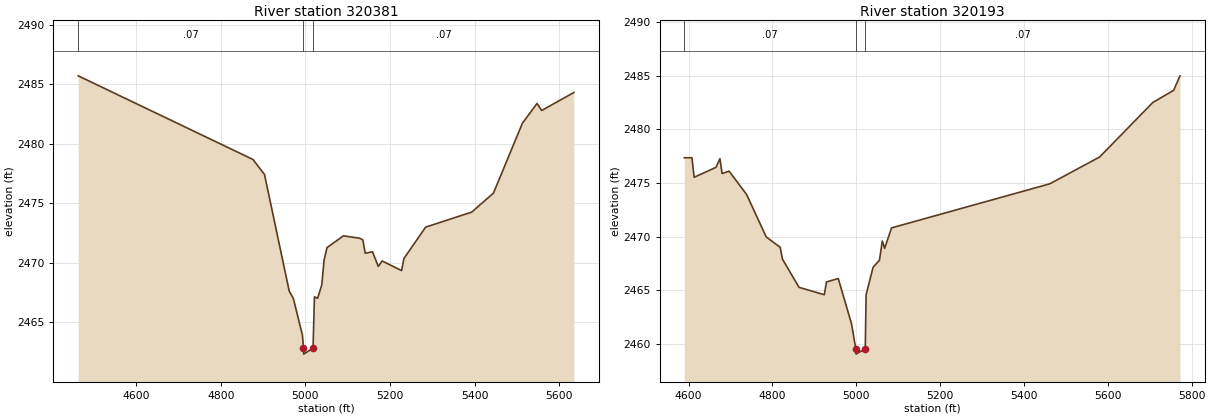
Type RM Length L Ch R = 1,320381,188,188,188
BEGIN DESCRIPTION:
Sweetwater Creek 639.0
END DESCRIPTION:
XS GIS Cut Line= 3
      1362807.94      6785825.86      1363081.81      6785364.30
      1363349.41      6784789.10
#Sta/Elev= 30
  4463.3 2485.70  4876.2 2478.68  4903.5 2477.42  4961.9 2467.63  4971.7 2467.01
  4993.2 2463.92  4995.6 2462.84  4996.1 2462.34  5018.2 2462.84  5021.5 2467.15
  5029.0 2467.03  5038.8 2468.15  5044.3 2470.24  5051.1 2471.28  5090.1 2472.27
  5128.3 2472.07  5135.9 2471.93  5141.4 2470.81  5158.7 2470.93  5172.4 2469.70
  5181.6 2470.16  5227.4 2469.35  5232.9 2470.36  5284.2 2473.00  5393.0 2474.26
  5444.4 2475.85  5513.0 2481.73  5547.4 2483.38  5558.4 2482.79  5634.4 2484.30
#Mann=3,-1,0
  4463.3    0.07       0  4995.6    0.07       0  5018.2    0.07       0
Bank Sta=4995.6,5018.2
Exp/Cntr=0.3,0.1

Type RM Length L Ch R = 1,320193,693,693,693
BEGIN DESCRIPTION:
Sweetwater Creek 638.0
END DESCRIPTION:
XS GIS Cut Line= 3
      1363104.85      6785880.48      1363220.71      6785486.98
      1363578.62      6784802.73
#Sta/Elev= 30
  4589.8 2477.36  4608.0 2477.36  4613.2 2475.54  4665.4 2476.47  4674.7 2477.28
  4679.9 2475.89  4696.6 2476.11  4738.3 2473.94  4785.1 2469.98  4818.5 2469.01
  4823.7 2467.92  4863.4 2465.28  4923.7 2464.59  4928.9 2465.78  4957.0 2466.10
  4988.5 2461.90  4998.8 2459.55  4999.3 2459.05  5021.4 2459.55  5023.5 2464.59
  5040.0 2467.14  5055.3 2467.81  5062.1 2469.60  5067.7 2468.92  5084.1 2470.82
  5461.6 2474.93  5580.5 2477.43  5707.3 2482.51  5757.1 2483.65  5772.2 2485.00
#Mann=3,-1,0
  4589.8    0.07       0  4998.8    0.07       0  5021.4    0.07       0
Bank Sta=4998.8,5021.4
Exp/Cntr=0.3,0.1