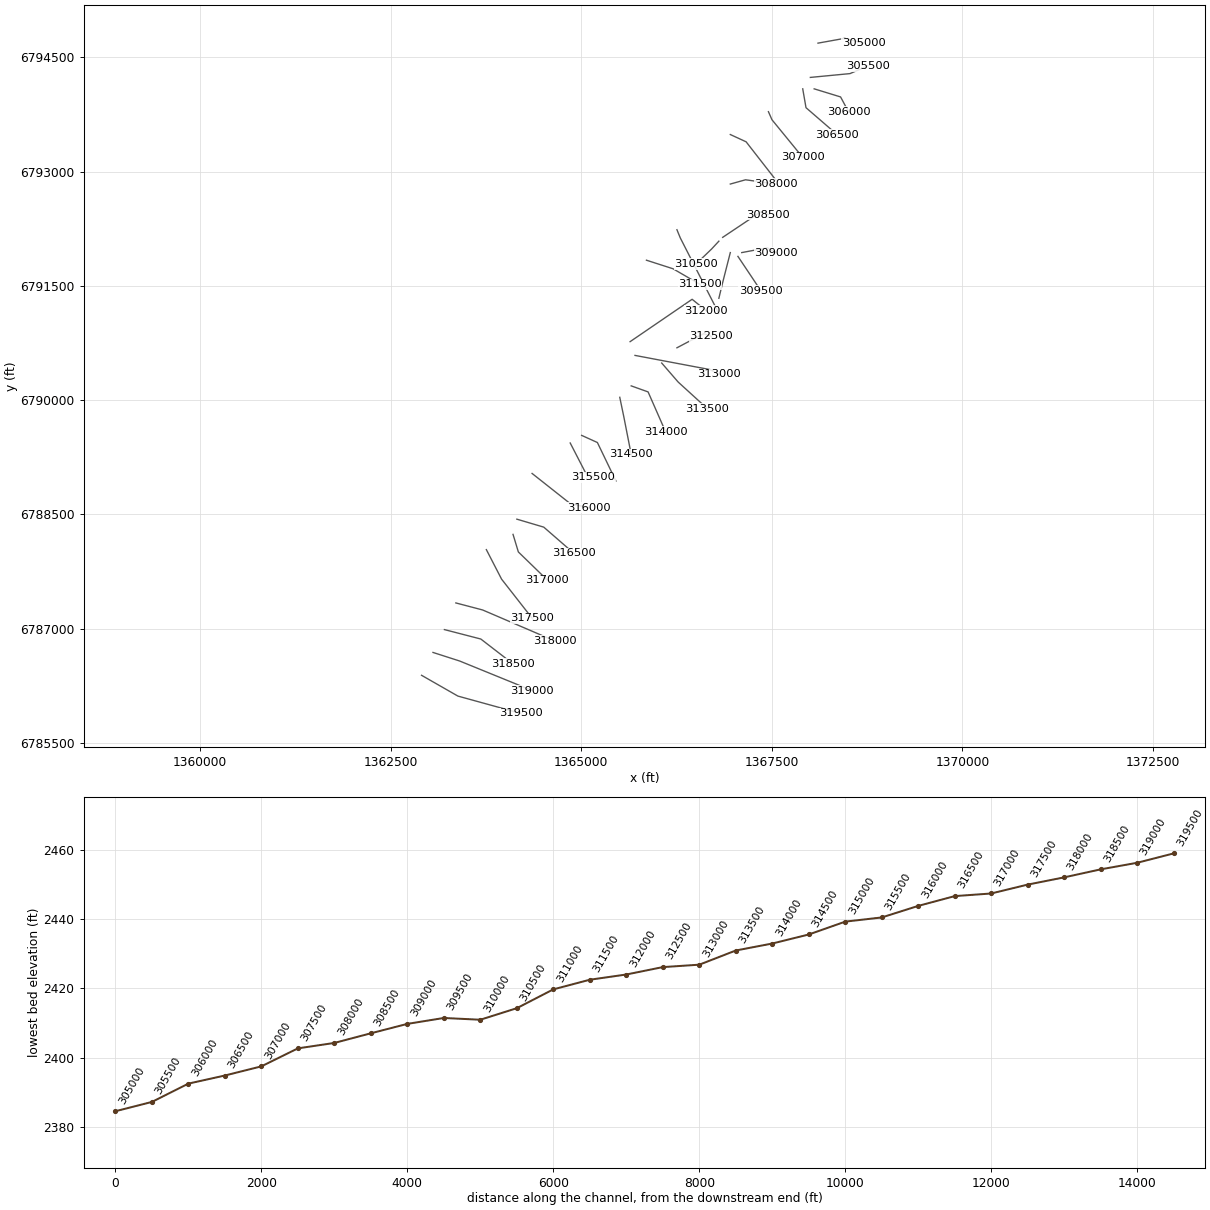
HEC-RAS study Sweetwater Creek.prj: Sweetwater Creek Base Level Engineering

--- Sweetwater Creek.g01 (geometry) --- (continued)

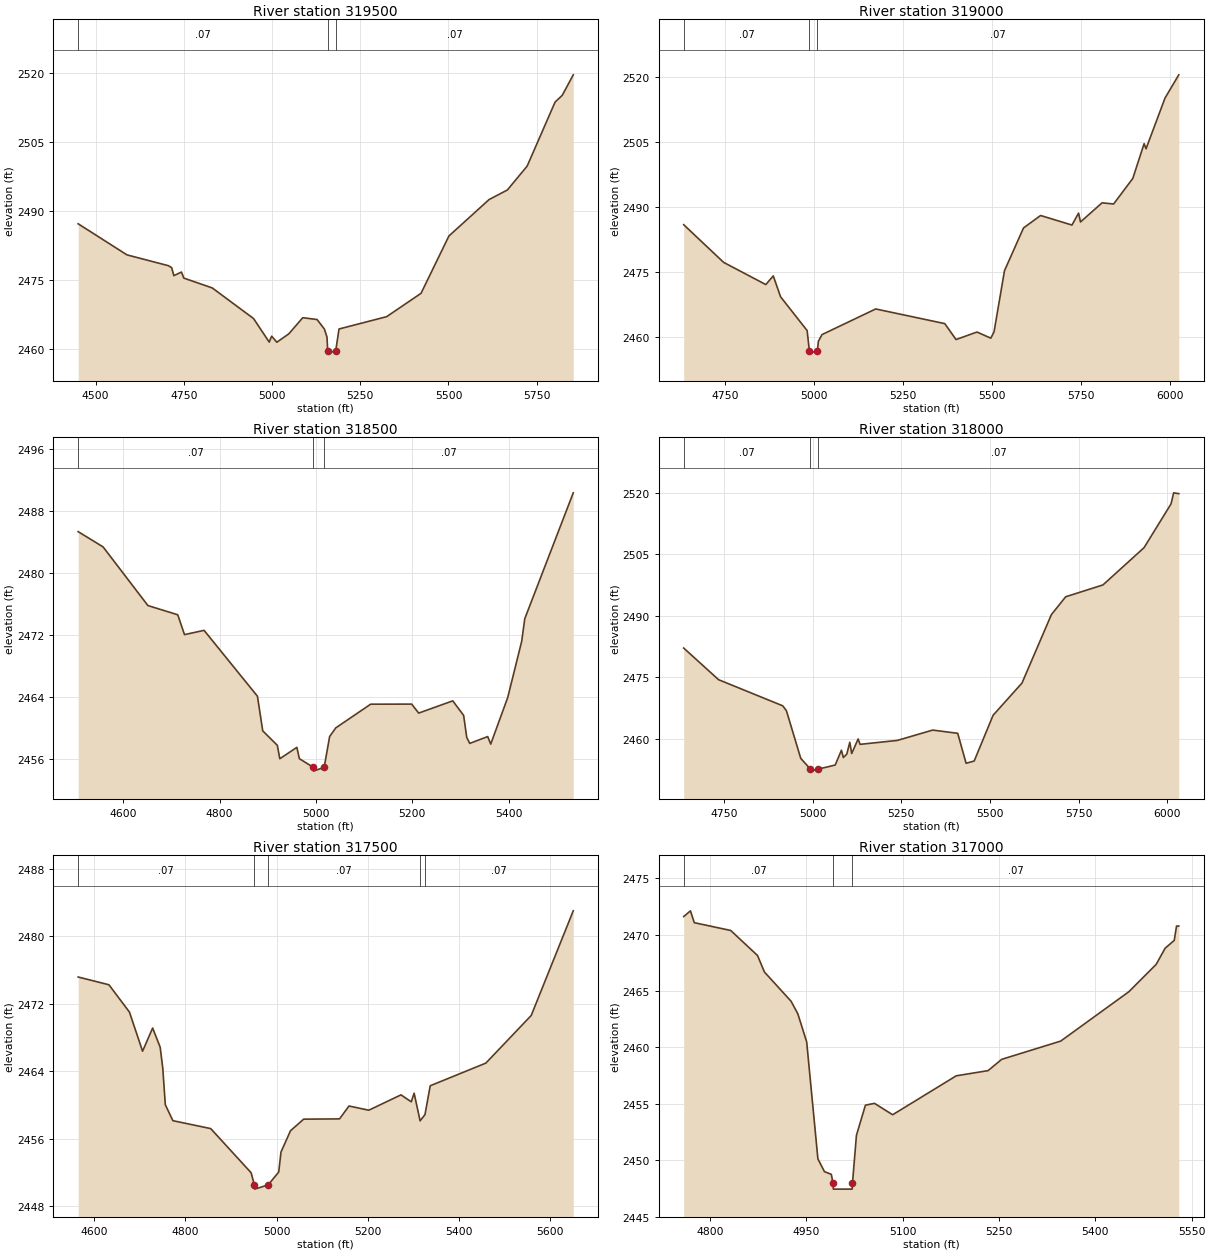
Type RM Length L Ch R = 1,319500,500,500,500
BEGIN DESCRIPTION:
Sweetwater Creek 637.0
END DESCRIPTION:
XS GIS Cut Line= 3
      1362905.03      6786387.98      1363381.93      6786115.01
      1364205.00      6785888.00
#Sta/Elev= 30
  4450.5 2487.17  4588.7 2480.41  4705.9 2478.06  4715.5 2477.63  4721.7 2475.89
  4743.3 2476.67  4750.1 2475.35  4830.7 2473.21  4947.7 2466.55  4992.0 2461.43
  4998.9 2462.72  5013.6 2461.40  5047.5 2463.22  5087.1 2466.74  5127.7 2466.34
  5148.4 2464.27  5155.8 2462.52  5157.8 2459.53  5158.3 2459.03  5180.5 2459.53
  5189.9 2464.28  5324.8 2466.96  5422.3 2472.04  5501.4 2484.52  5615.2 2492.44
  5667.1 2494.53  5723.2 2499.73  5802.3 2513.66  5822.7 2515.13  5853.8 2519.58
#Mann=3,-1,0
  4450.5    0.07       0  5157.8    0.07       0  5180.5    0.07       0
Bank Sta=5157.8,5180.5
Exp/Cntr=0.3,0.1

Type RM Length L Ch R = 1,319000,500,500,500
BEGIN DESCRIPTION:
Sweetwater Creek 636.0
END DESCRIPTION:
XS GIS Cut Line= 3
      1363054.98      6786688.01      1363404.92      6786575.46
      1364354.96      6786188.02
#Sta/Elev= 30
  4632.4 2485.92  4744.7 2477.24  4863.5 2472.12  4884.5 2474.12  4905.2 2469.29
  4979.9 2461.51  4986.1 2456.82  4986.6 2456.32  5008.8 2456.82  5011.4 2459.03
  5021.7 2460.59  5172.9 2466.50  5367.3 2463.12  5399.0 2459.45  5457.9 2461.18
  5496.9 2459.77  5506.0 2461.24  5535.4 2475.32  5588.9 2485.17  5637.0 2488.04
  5725.3 2485.84  5743.9 2488.59  5749.3 2486.55  5810.1 2490.96  5842.5 2490.69
  5896.5 2496.58  5928.4 2504.60  5933.8 2503.42  5987.3 2515.12  6026.0 2520.46
#Mann=3,-1,0
  4632.4    0.07       0  4986.1    0.07       0  5008.8    0.07       0
Bank Sta=4986.1,5008.8
Exp/Cntr=0.3,0.1

Type RM Length L Ch R = 1,318500,500,500,500
BEGIN DESCRIPTION:
Sweetwater Creek 635.0
END DESCRIPTION:
XS GIS Cut Line= 3
      1363204.98      6786988.01      1363682.48      6786864.16
      1364105.03      6786537.98
#Sta/Elev= 30
  4506.7 2485.33  4558.4 2483.36  4651.4 2475.79  4713.3 2474.60  4727.3 2472.04
  4767.9 2472.59  4878.6 2464.09  4889.6 2459.62  4919.9 2457.75  4925.0 2456.02
  4960.4 2457.49  4965.6 2456.03  4994.3 2454.92  4994.8 2454.42  5017.1 2454.92
  5028.4 2458.89  5041.1 2460.00  5113.5 2463.06  5198.6 2463.07  5213.1 2461.91
  5283.8 2463.49  5306.4 2461.61  5312.8 2458.77  5319.1 2458.00  5356.3 2458.88
  5362.6 2457.91  5397.9 2463.93  5426.9 2471.20  5433.2 2474.09  5533.8 2490.34
#Mann=3,-1,0
  4506.7    0.07       0  4994.3    0.07       0  5017.1    0.07       0
Bank Sta=4994.3,5017.1
Exp/Cntr=0.3,0.1

Type RM Length L Ch R = 1,318000,500,500,500
BEGIN DESCRIPTION:
Sweetwater Creek 634.0
END DESCRIPTION:
XS GIS Cut Line= 3
      1363354.96      6787338.01      1363706.60      6787245.52
      1364655.04      6786837.98
#Sta/Elev= 30
  4636.4 2482.12  4734.7 2474.40  4915.6 2468.03  4926.0 2466.84  4966.4 2455.22
  4993.6 2452.60  4994.1 2452.10  5016.4 2452.60  5063.6 2453.59  5081.1 2457.20
  5086.6 2455.42  5096.2 2456.24  5104.7 2459.14  5110.1 2456.39  5128.2 2459.95
  5133.7 2458.63  5238.8 2459.59  5338.4 2462.11  5409.0 2461.32  5432.6 2454.02
  5455.4 2454.56  5508.7 2465.72  5590.2 2473.58  5673.1 2490.27  5713.4 2494.62
  5818.5 2497.51  5934.3 2506.59  6010.5 2517.28  6017.8 2519.97  6032.3 2519.77
#Mann=3,-1,0
  4636.4    0.07       0  4993.6    0.07       0  5016.4    0.07       0
Bank Sta=4993.6,5016.4
Exp/Cntr=0.3,0.1

Type RM Length L Ch R = 1,317500,500,500,500
BEGIN DESCRIPTION:
Sweetwater Creek 633.0
END DESCRIPTION:
XS GIS Cut Line= 3
      1363755.01      6788037.98      1363954.35      6787650.89
      1364354.98      6787138.02
#Sta/Elev= 30
  4564.6 2475.17  4632.1 2474.25  4677.1 2471.01  4705.9 2466.37  4728.0 2469.12
  4744.5 2466.85  4750.2 2464.38  4755.8 2460.02  4772.4 2458.13  4855.4 2457.19
  4944.1 2451.95  4951.2 2450.51  4951.7 2450.01  4981.4 2450.51  5004.6 2452.04
  5009.6 2454.41  5030.4 2456.93  5059.3 2458.31  5138.0 2458.34  5158.8 2459.87
  5202.2 2459.37  5272.8 2461.19  5295.4 2460.37  5301.7 2461.39  5314.8 2458.11
  5325.5 2458.85  5337.0 2462.27  5459.1 2464.96  5558.6 2470.61  5650.8 2483.02
#Mann=5,-1,0
  4564.6    0.07       0  4951.2    0.07       0  4981.4    0.07       0
  5314.8    0.16       0  5325.5    0.07       0
Bank Sta=4951.2,4981.4
Exp/Cntr=0.3,0.1

Type RM Length L Ch R = 1,317000,500,500,500
BEGIN DESCRIPTION:
Sweetwater Creek 632.0
END DESCRIPTION:
XS GIS Cut Line= 3
      1364104.99      6788238.03      1364174.90      6788007.39
      1364554.98      6787638.01
#Sta/Elev= 30
  4759.0 2471.59  4769.5 2472.10  4775.5 2471.05  4832.2 2470.36  4874.0 2468.14
  4884.7 2466.68  4926.2 2464.09  4936.7 2462.98  4950.5 2460.49  4968.0 2450.12
  4978.2 2448.99  4988.9 2448.75  4991.6 2447.94  4992.1 2447.44  5021.3 2447.44
  5021.8 2447.94  5028.0 2452.21  5042.0 2454.88  5056.1 2455.04  5084.4 2454.03
  5183.4 2457.48  5233.0 2457.94  5254.2 2458.94  5346.2 2460.56  5452.2 2464.93
  5494.7 2467.35  5508.8 2468.79  5522.9 2469.48  5526.5 2470.75  5530.0 2470.75
#Mann=3,-1,0
  4759.0    0.07       0  4991.6    0.07       0  5021.8    0.07       0
Bank Sta=4991.6,5021.8
Exp/Cntr=0.3,0.1

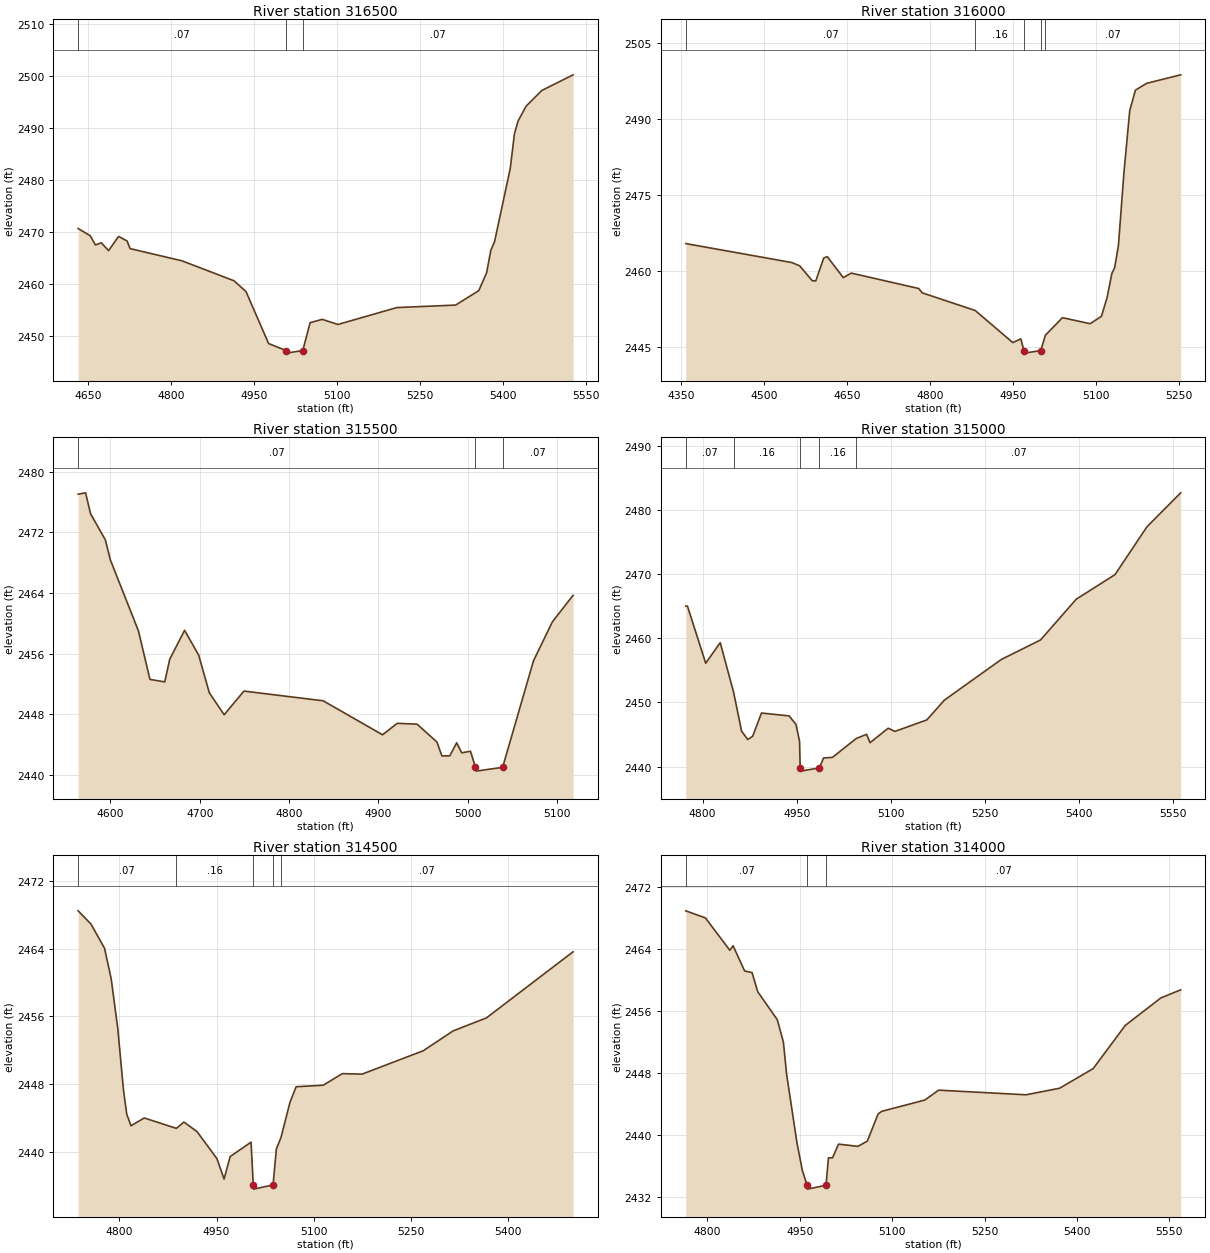
Type RM Length L Ch R = 1,316500,500,500,500
BEGIN DESCRIPTION:
Sweetwater Creek 631.0
END DESCRIPTION:
XS GIS Cut Line= 3
      1364155.01      6788438.00      1364508.00      6788333.27
      1364904.97      6787988.02
#Sta/Elev= 30
  4631.8 2470.67  4653.6 2469.28  4663.1 2467.50  4673.5 2467.92  4686.8 2466.42
  4704.8 2469.15  4720.1 2468.28  4725.7 2466.80  4819.5 2464.45  4913.4 2460.61
  4935.1 2458.53  4976.0 2448.52  5007.4 2447.18  5007.9 2446.68  5037.7 2447.18
  5050.9 2452.54  5072.8 2453.18  5101.2 2452.20  5207.6 2455.45  5313.9 2455.93
  5355.7 2458.71  5369.9 2462.17  5377.5 2466.49  5384.2 2468.11  5412.7 2482.32
  5420.1 2488.89  5426.9 2491.41  5441.2 2494.22  5469.6 2497.25  5526.1 2500.26
#Mann=3,-1,0
  4631.8    0.07       0  5007.4    0.07       0  5037.7    0.07       0
Bank Sta=5007.4,5037.7
Exp/Cntr=0.3,0.1

Type RM Length L Ch R = 1,316000,500,500,500
BEGIN DESCRIPTION:
Sweetwater Creek 630.0
END DESCRIPTION:
XS GIS Cut Line= 3
      1364355.03      6789037.98      1364857.63      6788640.31
      1365104.96      6788588.01
#Sta/Elev= 30
  4359.1 2465.45  4550.6 2461.71  4565.0 2461.05  4587.5 2458.13  4593.9 2458.09
  4608.3 2462.62  4614.7 2462.87  4643.5 2458.74  4658.0 2459.63  4779.8 2456.59
  4786.2 2455.73  4881.7 2452.26  4949.7 2445.93  4964.1 2446.66  4969.8 2444.35
  4970.3 2443.85  5000.1 2444.35  5008.5 2447.37  5039.3 2450.84  5089.3 2449.65
  5109.7 2451.11  5120.0 2454.82  5128.5 2459.53  5133.6 2460.70  5140.4 2465.08
  5150.6 2479.73  5160.8 2491.65  5171.1 2495.70  5191.5 2497.05  5252.8 2498.72
#Mann=5,-1,0
  4359.1    0.07       0  4881.7    0.16       0  4969.8    0.07       0
  5000.1    0.16       0  5008.5    0.07       0
Bank Sta=4969.8,5000.1
Exp/Cntr=0.3,0.1

Type RM Length L Ch R = 1,315500,500,500,500
BEGIN DESCRIPTION:
Sweetwater Creek 629.0
END DESCRIPTION:
XS GIS Cut Line= 3
      1364854.99      6789438.01      1365054.62      6789050.17
      1365155.02      6788987.99
#Sta/Elev= 30
  4563.8 2477.01  4572.1 2477.19  4577.7 2474.43  4594.3 2470.98  4599.9 2468.34
  4631.3 2459.00  4644.2 2452.60  4660.8 2452.27  4666.4 2455.27  4683.0 2459.07
  4698.8 2455.79  4710.7 2450.84  4727.3 2447.94  4749.5 2451.06  4838.2 2449.78
  4904.7 2445.30  4921.2 2446.81  4943.4 2446.70  4965.6 2444.35  4971.2 2442.52
  4980.0 2442.52  4987.7 2444.24  4993.4 2442.92  5003.2 2443.13  5008.8 2441.01
  5009.3 2440.51  5039.2 2441.01  5073.8 2455.06  5095.0 2460.20  5118.1 2463.68
#Mann=3,-1,0
  4563.8    0.07       0  5008.8    0.07       0  5039.2    0.07       0
Bank Sta=5008.8,5039.2
Exp/Cntr=0.3,0.1

Type RM Length L Ch R = 1,315000,500,500,500
BEGIN DESCRIPTION:
Sweetwater Creek 628.0
END DESCRIPTION:
XS GIS Cut Line= 3
      1365005.04      6789537.98      1365211.50      6789444.34
      1365454.98      6788938.04
#Sta/Elev= 30
  4773.3 2465.00  4776.0 2465.00  4805.1 2456.11  4828.2 2459.31  4849.5 2451.60
  4862.3 2445.52  4872.1 2444.22  4879.9 2444.73  4894.0 2448.35  4938.0 2447.90
  4948.9 2446.58  4954.6 2443.96  4955.6 2439.80  4956.1 2439.30  4986.2 2439.80
  4992.9 2441.35  5007.0 2441.44  5045.2 2444.40  5061.4 2445.03  5066.9 2443.73
  5095.8 2445.98  5106.6 2445.49  5157.4 2447.28  5185.6 2450.38  5276.2 2456.70
  5338.5 2459.73  5395.4 2466.08  5457.2 2469.91  5508.0 2477.35  5561.8 2482.65
#Mann=5,-1,0
  4773.3    0.07       0  4849.5    0.16       0  4955.6    0.07       0
  4986.2    0.16       0  5045.2    0.07       0
Bank Sta=4955.6,4986.2
Exp/Cntr=0.3,0.1

Type RM Length L Ch R = 1,314500,500,500,500
BEGIN DESCRIPTION:
Sweetwater Creek 627.0
END DESCRIPTION:
XS GIS Cut Line= 3
      1365505.01      6790037.96      1365558.67      6789779.67
      1365655.00      6789288.02
#Sta/Elev= 30
  4736.2 2468.47  4756.1 2466.90  4777.0 2464.04  4787.2 2460.46  4797.4 2454.58
  4806.2 2447.32  4811.3 2444.42  4817.9 2443.07  4838.3 2443.99  4888.0 2442.76
  4899.6 2443.51  4920.0 2442.37  4950.6 2439.19  4961.7 2436.77  4971.1 2439.43
  5003.4 2441.13  5006.8 2436.08  5007.3 2435.58  5037.4 2436.08  5042.5 2440.33
  5049.6 2441.67  5063.4 2445.80  5073.0 2447.68  5114.9 2447.86  5144.4 2449.23
  5174.9 2449.17  5269.4 2451.93  5315.7 2454.28  5367.2 2455.82  5501.0 2463.63
#Mann=5,-1,0
  4736.2    0.07       0  4888.0    0.16       0  5006.8    0.07       0
  5037.4    0.16       0  5049.6    0.07       0
Bank Sta=5006.8,5037.4
Exp/Cntr=0.3,0.1

Type RM Length L Ch R = 1,314000,500,500,500
BEGIN DESCRIPTION:
Sweetwater Creek 626.0
END DESCRIPTION:
XS GIS Cut Line= 3
      1365654.99      6790188.00      1365876.51      6790108.66
      1366105.01      6789587.99
#Sta/Elev= 30
  4764.7 2468.96  4796.6 2468.05  4836.3 2463.86  4841.6 2464.44  4860.3 2461.19
  4872.4 2460.97  4881.6 2458.50  4913.4 2454.88  4923.3 2451.98  4928.6 2447.79
  4945.3 2438.98  4954.0 2435.42  4961.8 2433.47  4962.3 2432.97  4992.5 2433.47
  4996.5 2437.02  5003.1 2437.02  5012.9 2438.79  5044.4 2438.50  5059.6 2439.18
  5077.2 2442.69  5083.0 2443.03  5153.1 2444.49  5175.4 2445.77  5317.4 2445.17
  5372.0 2446.02  5426.4 2448.55  5478.6 2454.14  5536.3 2457.69  5568.6 2458.74
#Mann=3,-1,0
  4764.7    0.07       0  4961.8    0.07       0  4992.5    0.07       0
Bank Sta=4961.8,4992.5
Exp/Cntr=0.3,0.1

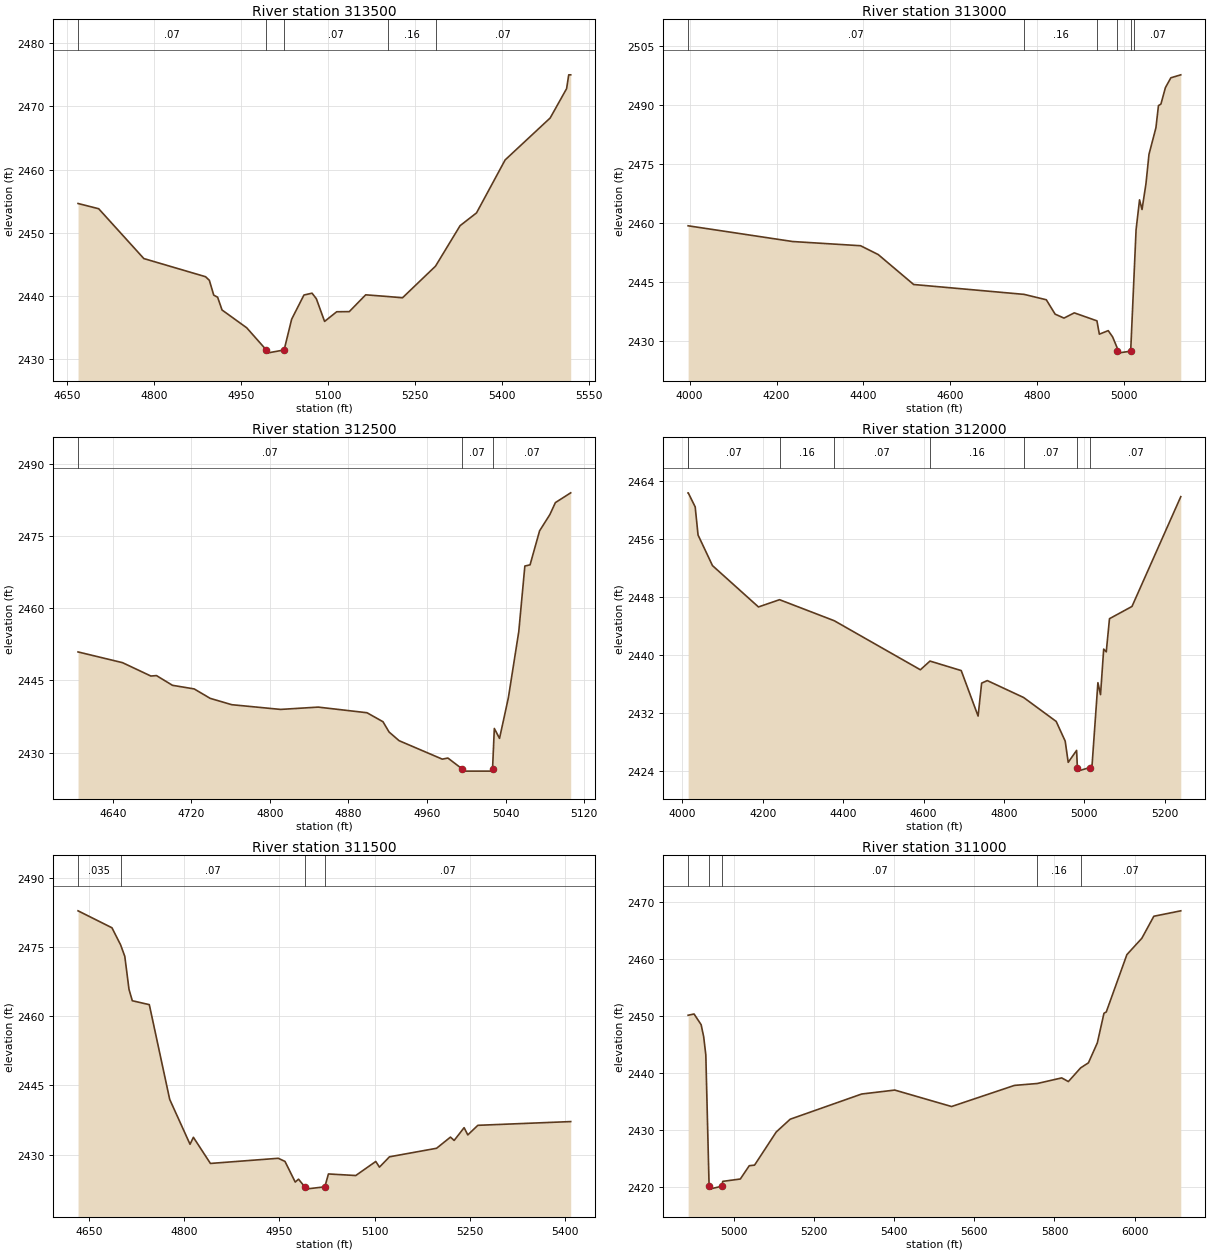
Type RM Length L Ch R = 1,313500,500,500,500
BEGIN DESCRIPTION:
Sweetwater Creek 625.0
END DESCRIPTION:
XS GIS Cut Line= 3
      1366055.00      6790487.99      1366271.69      6790237.64
      1366654.98      6789888.02
#Sta/Elev= 30
  4668.9 2454.64  4704.5 2453.81  4782.4 2445.92  4888.8 2443.05  4895.4 2442.48
  4903.0 2440.13  4909.7 2439.80  4917.3 2437.78  4959.9 2434.96  4993.7 2431.45
  4994.2 2430.95  5024.4 2431.45  5037.4 2436.32  5058.6 2440.15  5072.6 2440.44
  5080.0 2439.56  5094.2 2435.97  5115.1 2437.50  5136.8 2437.52  5165.1 2440.18
  5203.5 2439.91  5228.6 2439.71  5285.6 2444.72  5328.0 2451.13  5356.3 2453.15
  5405.7 2461.54  5483.4 2468.18  5511.7 2472.82  5515.4 2475.01  5518.8 2475.01
#Mann=5,-1,0
  4668.9    0.07       0  4993.7    0.07       0  5024.4    0.07       0
  5203.5    0.16       0  5285.6    0.07       0
Bank Sta=4993.7,5024.4
Exp/Cntr=0.3,0.1

Type RM Length L Ch R = 1,313000,500,500,500
BEGIN DESCRIPTION:
Sweetwater Creek 624.0
END DESCRIPTION:
XS GIS Cut Line= 3
      1365705.00      6790588.00      1366691.00      6790401.36
      1366804.98      6790338.01
#Sta/Elev= 30
  3996.5 2459.23  4237.1 2455.23  4393.4 2454.16  4434.1 2451.91  4515.6 2444.30
  4769.7 2441.79  4820.9 2440.42  4841.2 2436.76  4861.6 2435.76  4885.3 2437.09
  4937.4 2435.06  4943.0 2431.67  4963.4 2432.57  4973.5 2430.98  4983.7 2428.27
  4983.9 2427.35  4984.4 2426.85  5015.1 2427.35  5022.6 2445.99  5027.5 2458.22
  5035.5 2465.83  5041.2 2463.37  5050.3 2469.96  5057.2 2477.39  5073.2 2484.16
  5079.0 2489.78  5084.7 2490.18  5095.0 2494.36  5107.5 2496.86  5130.4 2497.62
#Mann=6,-1,0
  3996.5    0.07       0  4769.7    0.16       0  4937.4    0.07       0
  4983.9    0.07       0  5015.1    0.07       0  5022.6    0.07       0
Bank Sta=4983.9,5015.1
Exp/Cntr=0.3,0.1

Type RM Length L Ch R = 1,312500,500,500,500
BEGIN DESCRIPTION:
Sweetwater Creek 623.0
END DESCRIPTION:
XS GIS Cut Line= 3
      1366254.96      6790687.98      1366604.47      6790872.87
      1366704.99      6790838.00
#Sta/Elev= 30
  4604.6 2450.93  4649.9 2448.70  4678.8 2445.92  4684.5 2446.01  4700.8 2443.99
  4722.9 2443.24  4739.2 2441.28  4761.2 2439.96  4810.9 2438.98  4849.2 2439.46
  4898.9 2438.29  4915.2 2436.42  4921.4 2434.28  4931.6 2432.48  4975.6 2428.64
  4981.3 2428.87  4995.6 2426.65  4996.1 2426.15  5026.3 2426.15  5026.8 2426.65
  5028.6 2435.02  5033.9 2432.96  5042.9 2441.40  5053.5 2455.16  5059.7 2468.79
  5065.0 2469.04  5074.7 2476.11  5085.2 2479.50  5090.8 2481.98  5106.4 2484.01
#Mann=3,-1,0
  4604.6    0.07       0  4995.6    0.07       0  5026.8    0.07       0
Bank Sta=4995.6,5026.8
Exp/Cntr=0.3,0.1

Type RM Length L Ch R = 1,312000,500,500,500
BEGIN DESCRIPTION:
Sweetwater Creek 622.0
END DESCRIPTION:
XS GIS Cut Line= 3
      1365640.51      6790768.48      1366454.21      6791324.80
      1366640.81      6791173.71
#Sta/Elev= 30
  4014.3 2462.37  4014.6 2462.37  4031.9 2460.43  4039.0 2456.56  4074.9 2452.34
  4189.3 2446.64  4241.8 2447.64  4377.9 2444.74  4592.2 2437.98  4616.1 2439.18
  4693.8 2437.87  4735.8 2431.60  4744.6 2436.14  4758.7 2436.49  4849.0 2434.16
  4930.1 2430.86  4952.5 2428.15  4960.0 2425.22  4980.9 2426.87  4982.8 2424.51
  4983.3 2424.01  5014.0 2424.51  5019.5 2424.93  5033.9 2436.20  5040.4 2434.55
  5048.3 2440.83  5054.7 2440.45  5062.7 2445.02  5118.7 2446.71  5240.1 2461.84
#Mann=8,-1,0
  4014.3   0.035       0  4014.6    0.07       0  4241.8    0.16       0
  4377.9    0.07       0  4616.1    0.16       0  4849.0    0.07       0
  4982.8    0.07       0  5014.0    0.07       0
Bank Sta=4982.8,5014
Exp/Cntr=0.3,0.1

Type RM Length L Ch R = 1,311500,500,500,500
BEGIN DESCRIPTION:
Sweetwater Creek 621.0
END DESCRIPTION:
XS GIS Cut Line= 3
      1365854.96      6791838.01      1366204.07      6791725.46
      1366557.66      6791520.30
#Sta/Elev= 30
  4633.2 2482.86  4686.6 2479.18  4700.2 2475.48  4706.8 2472.98  4713.4 2465.84
  4718.6 2463.36  4745.4 2462.51  4777.5 2441.96  4809.5 2432.23  4814.8 2433.74
  4841.6 2428.07  4948.4 2429.19  4959.0 2428.51  4975.1 2424.03  4980.3 2424.66
  4990.1 2423.00  4990.6 2422.50  5021.7 2423.00  5027.4 2425.79  5070.4 2425.45
  5101.9 2428.50  5107.7 2427.27  5123.5 2429.51  5197.6 2431.36  5219.5 2433.78
  5225.3 2433.06  5241.0 2435.83  5246.8 2434.26  5262.6 2436.34  5408.8 2437.15
#Mann=4,-1,0
  4633.2   0.035       0  4700.2    0.07       0  4990.1    0.07       0
  5021.7    0.07       0
Bank Sta=4990.1,5021.7
Exp/Cntr=0.3,0.1

Type RM Length L Ch R = 1,311000,500,500,500
BEGIN DESCRIPTION:
Sweetwater Creek 620.0
END DESCRIPTION:
XS GIS Cut Line= 3
      1366254.98      6792238.04      1366298.42      6792131.77
      1366804.98      6791138.04
#Sta/Elev= 30
  4885.2 2450.15  4900.0 2450.37  4917.7 2448.50  4924.0 2446.41  4929.4 2443.20
  4937.6 2420.21  4938.1 2419.71  4969.2 2420.21  4971.7 2421.07  5015.5 2421.48
  5037.9 2423.81  5051.1 2423.91  5105.3 2429.72  5140.1 2431.95  5318.5 2436.36
  5401.3 2437.05  5543.0 2434.17  5700.1 2437.87  5757.0 2438.20  5818.1 2439.18
  5834.7 2438.54  5865.4 2440.94  5884.8 2441.82  5907.0 2445.31  5923.6 2450.50
  5929.3 2450.72  5980.8 2460.76  6018.2 2463.63  6048.1 2467.48  6115.4 2468.43
#Mann=5,-1,0
  4885.2    0.07       0  4937.6    0.07       0  4969.2    0.07       0
  5757.0    0.16       0  5865.4    0.07       0
Bank Sta=4937.6,4969.2
Exp/Cntr=0.3,0.1

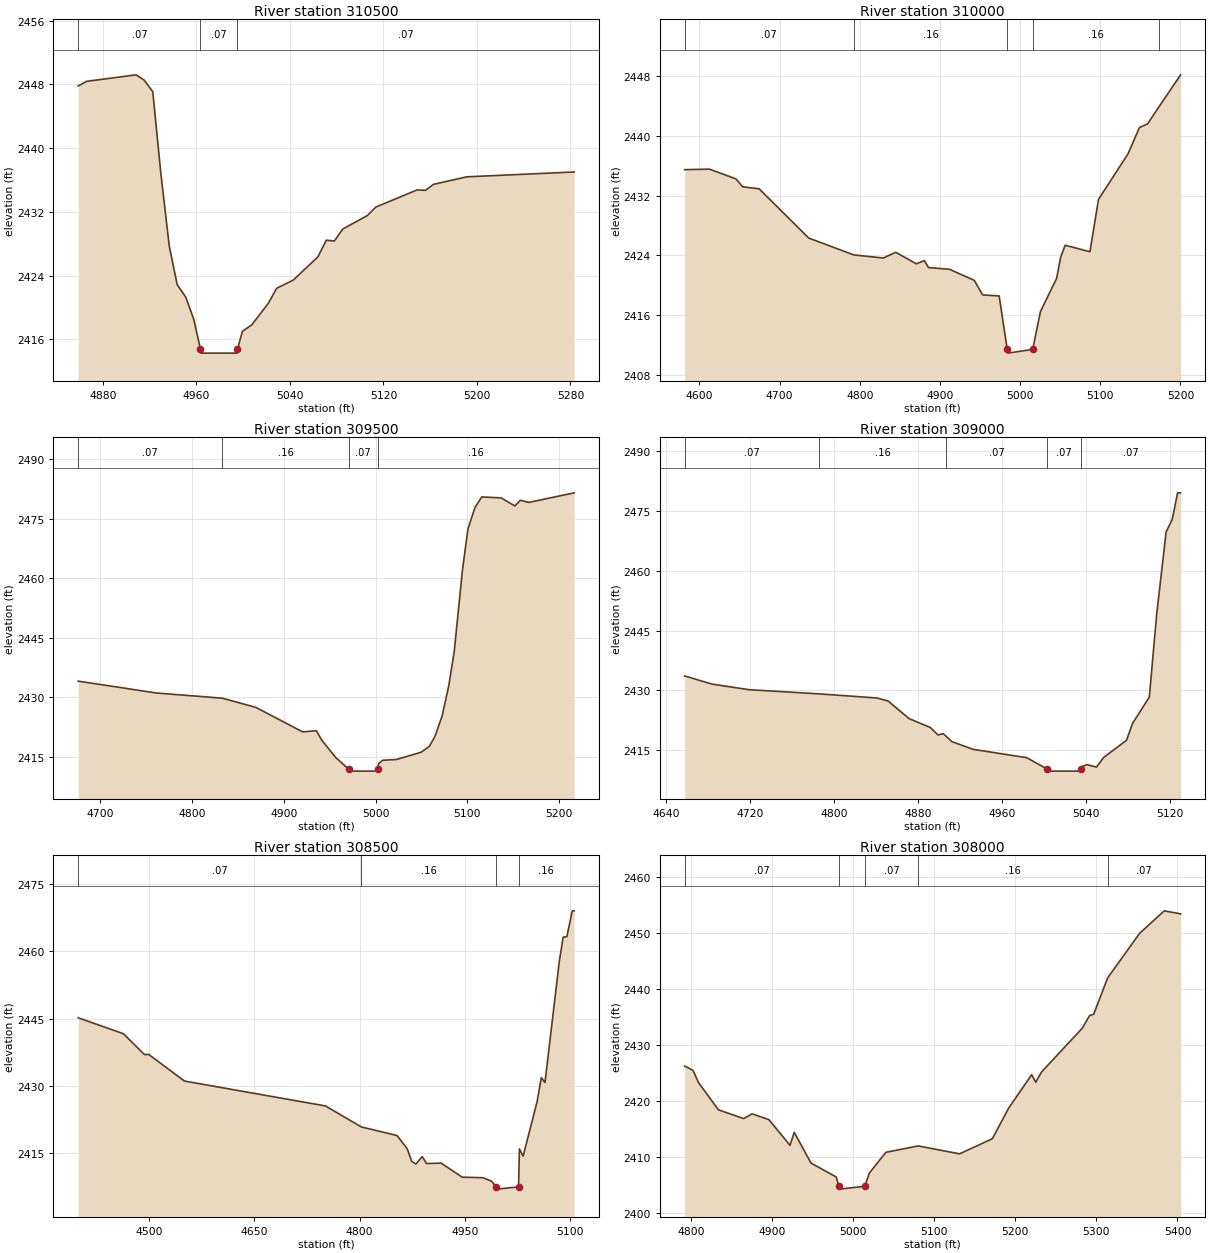
Type RM Length L Ch R = 1,310500,500,500,500
BEGIN DESCRIPTION:
Sweetwater Creek 619.0
END DESCRIPTION:
XS GIS Cut Line= 3
      1366804.99      6792087.99      1366708.98      6791984.45
      1366505.00      6791788.00
#Sta/Elev= 30
  4858.8 2447.79  4865.9 2448.37  4908.4 2449.19  4915.2 2448.53  4922.6 2447.07
  4929.4 2436.99  4936.7 2427.72  4943.5 2422.87  4950.9 2421.28  4957.7 2418.51
  4963.4 2414.77  4963.9 2414.27  4994.6 2414.27  4995.1 2414.77  4999.3 2417.00
  5007.3 2417.82  5021.4 2420.50  5028.6 2422.40  5042.8 2423.43  5063.9 2426.35
  5071.1 2428.44  5078.0 2428.34  5085.2 2429.84  5106.3 2431.54  5113.5 2432.60
  5148.8 2434.75  5156.0 2434.70  5162.9 2435.45  5191.2 2436.39  5283.2 2437.00
#Mann=3,-1,0
  4858.8    0.07       0  4963.4    0.07       0  4995.1    0.07       0
Bank Sta=4963.4,4995.1
Exp/Cntr=0.3,0.1

Type RM Length L Ch R = 1,310000,500,500,500
BEGIN DESCRIPTION:
Sweetwater Creek 618.0
END DESCRIPTION:
XS GIS Cut Line= 3
      1366955.01      6791938.04      1366851.69      6791532.70
      1366805.00      6791338.02
#Sta/Elev= 30
  4581.7 2435.46  4612.7 2435.53  4645.6 2434.23  4654.0 2433.17  4674.6 2432.90
  4736.5 2426.31  4792.7 2424.06  4829.4 2423.65  4844.9 2424.41  4870.7 2422.87
  4880.6 2423.30  4885.8 2422.37  4912.0 2422.14  4942.9 2420.66  4953.3 2418.71
  4973.9 2418.58  4984.0 2411.43  4984.5 2410.93  5015.7 2411.43  5025.4 2416.49
  5045.5 2420.91  5050.6 2423.75  5056.2 2425.35  5087.1 2424.49  5097.8 2431.49
  5134.6 2437.57  5148.8 2441.08  5159.1 2441.60  5173.4 2443.89  5200.2 2448.14
#Mann=5,-1,0
  4581.7    0.07       0  4792.7    0.16       0  4984.0    0.07       0
  5015.7    0.16       0  5173.4    0.07       0
Bank Sta=4984,5015.7
Exp/Cntr=0.3,0.1

Type RM Length L Ch R = 1,309500,500,500,500
BEGIN DESCRIPTION:
Sweetwater Creek 617.0
END DESCRIPTION:
XS GIS Cut Line= 3
      1367055.02      6791887.97      1367235.26      6791618.37
      1367355.00      6791438.00
#Sta/Elev= 30
  4675.7 2434.11  4761.3 2431.11  4832.8 2429.82  4869.4 2427.50  4920.4 2421.33
  4935.4 2421.61  4941.4 2419.20  4956.5 2414.88  4970.6 2411.94  4971.1 2411.44
  5001.9 2411.44  5002.4 2411.94  5003.2 2413.34  5007.5 2414.17  5022.6 2414.37
  5049.6 2416.20  5058.6 2417.69  5064.6 2420.12  5072.5 2425.31  5079.7 2432.86
  5085.7 2441.48  5094.7 2462.12  5100.7 2472.49  5108.5 2477.93  5115.8 2480.52
  5136.8 2480.28  5151.9 2478.25  5157.9 2479.68  5166.9 2479.13  5216.5 2481.55
#Mann=4,-1,0
  4675.7    0.07       0  4832.8    0.16       0  4970.6    0.07       0
  5002.4    0.16       0
Bank Sta=4970.6,5002.4
Exp/Cntr=0.3,0.1

Type RM Length L Ch R = 1,309000,500,500,500
BEGIN DESCRIPTION:
Sweetwater Creek 616.0
END DESCRIPTION:
XS GIS Cut Line= 3
      1367105.02      6791938.00      1367441.12      6792001.24
      1367555.03      6791937.98
#Sta/Elev= 30
  4658.0 2433.63  4684.2 2431.58  4719.0 2430.19  4786.1 2429.13  4841.1 2428.10
  4851.8 2427.34  4871.7 2422.92  4892.0 2420.68  4899.2 2418.81  4904.3 2419.13
  4907.3 2418.40  4912.4 2417.15  4932.7 2415.20  4983.6 2413.12  5003.4 2410.23
  5003.9 2409.73  5034.7 2409.73  5035.2 2410.23  5035.3 2410.75  5041.0 2411.35
  5050.2 2410.75  5057.0 2413.17  5078.8 2417.48  5084.5 2421.70  5100.5 2428.31
  5107.4 2448.86  5116.5 2469.81  5122.3 2472.93  5127.4 2479.62  5130.3 2479.62
#Mann=5,-1,0
  4658.0    0.07       0  4786.1    0.16       0  4907.3    0.07       0
  5003.4    0.07       0  5035.2    0.07       0
Bank Sta=5003.4,5035.2
Exp/Cntr=0.3,0.1

Type RM Length L Ch R = 1,308500,500,500,500
BEGIN DESCRIPTION:
Sweetwater Creek 615.0
END DESCRIPTION:
XS GIS Cut Line= 3
      1366855.02      6792138.01      1367354.64      6792472.59
      1367455.04      6792437.99
#Sta/Elev= 30
  4398.7 2445.17  4463.2 2441.62  4493.2 2436.98  4499.2 2437.02  4550.3 2431.08
  4751.4 2425.54  4802.6 2420.86  4853.5 2418.95  4868.0 2416.02  4874.5 2413.20
  4880.5 2412.62  4889.5 2414.26  4895.5 2412.71  4916.5 2412.80  4946.5 2409.67
  4976.4 2409.55  4988.6 2408.76  4995.1 2407.51  4995.6 2407.01  5026.9 2407.51
  5028.1 2415.96  5033.4 2414.36  5053.3 2426.46  5059.3 2431.83  5064.6 2430.77
  5085.0 2457.71  5090.5 2463.12  5095.8 2463.24  5103.5 2468.99  5106.2 2468.99
#Mann=4,-1,0
  4398.7    0.07       0  4802.6    0.16       0  4995.1    0.07       0
  5026.9    0.16       0
Bank Sta=4995.1,5026.9
Exp/Cntr=0.3,0.1

Type RM Length L Ch R = 1,308000,500,500,500
BEGIN DESCRIPTION:
Sweetwater Creek 614.0
END DESCRIPTION:
XS GIS Cut Line= 3
      1366954.97      6792837.99      1367155.00      6792893.92
      1367555.01      6792838.00
#Sta/Elev= 30
  4792.3 2426.19  4802.7 2425.41  4809.4 2423.22  4833.9 2418.38  4865.0 2416.81
  4875.4 2417.66  4896.2 2416.62  4922.2 2412.04  4927.4 2414.37  4948.1 2408.87
  4979.2 2406.39  4982.4 2404.72  4982.9 2404.22  5014.2 2404.72  5020.2 2407.12
  5040.4 2410.79  5080.3 2411.93  5131.3 2410.52  5171.7 2413.21  5191.9 2418.69
  5220.2 2424.64  5225.3 2423.30  5232.2 2425.10  5282.7 2432.95  5291.7 2435.21
  5296.7 2435.43  5314.0 2441.95  5353.4 2449.88  5383.7 2453.89  5403.9 2453.35
#Mann=5,-1,0
  4792.3    0.07       0  4982.4    0.07       0  5014.2    0.07       0
  5080.3    0.16       0  5314.0    0.07       0
Bank Sta=4982.4,5014.2
Exp/Cntr=0.3,0.1

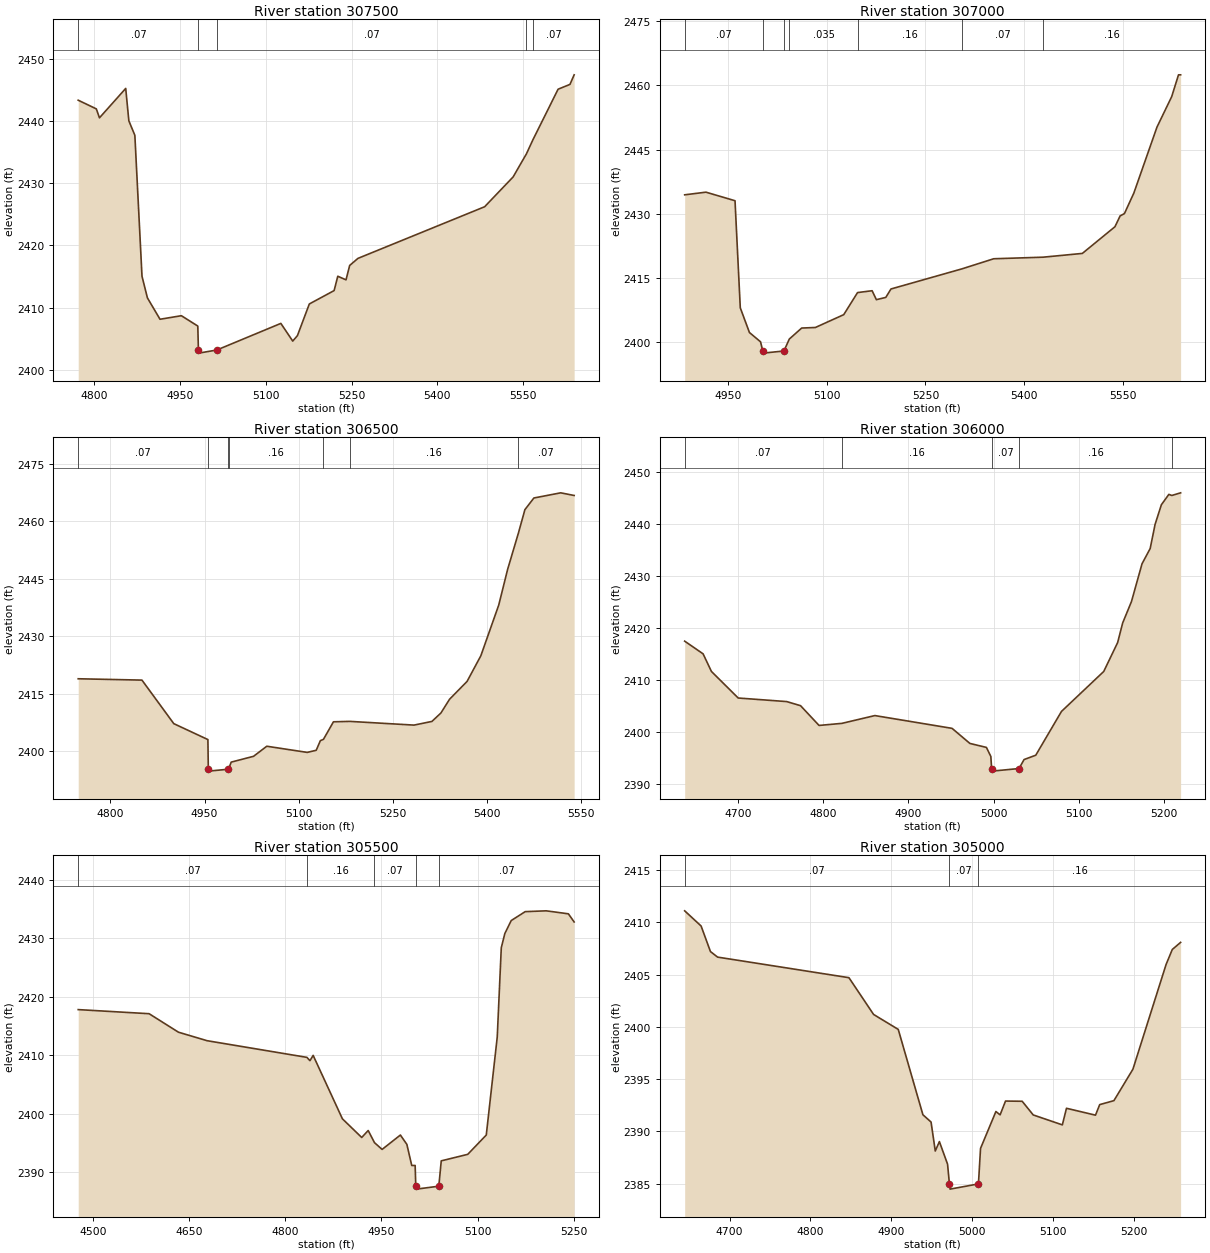
Type RM Length L Ch R = 1,307500,500,500,500
BEGIN DESCRIPTION:
Sweetwater Creek 613.0
END DESCRIPTION:
XS GIS Cut Line= 3
      1366955.00      6793488.00      1367162.18      6793392.58
      1367555.03      6792887.97
#Sta/Elev= 30
  4771.9 2443.41  4803.6 2442.01  4809.1 2440.57  4855.0 2445.31  4860.5 2440.09
  4871.0 2437.75  4883.5 2415.03  4893.0 2411.55  4915.0 2408.11  4952.4 2408.68
  4981.1 2407.01  4982.2 2403.15  4982.7 2402.65  5014.3 2403.15  5126.4 2407.44
  5147.2 2404.59  5155.4 2405.47  5176.2 2410.57  5219.6 2412.73  5226.0 2415.04
  5240.4 2414.46  5246.8 2416.78  5261.3 2417.92  5482.9 2426.24  5532.7 2431.04
  5556.1 2434.78  5567.1 2436.98  5611.4 2445.18  5632.2 2445.96  5639.5 2447.50
#Mann=5,-1,0
  4771.9    0.07       0  4982.2    0.07       0  5014.3    0.07       0
  5556.1    0.16       0  5567.1    0.07       0
Bank Sta=4982.2,5014.3
Exp/Cntr=0.3,0.1

Type RM Length L Ch R = 1,307000,500,500,500
BEGIN DESCRIPTION:
Sweetwater Creek 612.0
END DESCRIPTION:
XS GIS Cut Line= 3
      1367454.98      6793788.04      1367501.62      6793681.94
      1367904.99      6793188.02
#Sta/Elev= 30
  4884.1 2434.44  4916.4 2435.06  4960.6 2433.06  4968.6 2408.04  4982.5 2402.27
  4999.4 2400.09  5002.8 2397.95  5003.3 2397.45  5034.9 2397.95  5043.1 2400.74
  5061.9 2403.31  5082.7 2403.44  5125.8 2406.44  5146.8 2411.60  5168.9 2412.03
  5175.4 2409.94  5189.7 2410.47  5197.6 2412.44  5305.2 2417.13  5353.7 2419.50
  5428.9 2419.87  5488.4 2420.75  5537.9 2426.98  5545.8 2429.52  5552.3 2430.05
  5566.6 2434.84  5601.8 2450.27  5624.1 2457.37  5634.5 2462.48  5637.7 2462.48
#Mann=7,-1,0
  4884.1    0.07       0  5002.8    0.07       0  5034.9    0.07       0
  5043.1   0.035       0  5146.8    0.16       0  5305.2    0.07       0
  5428.9    0.16       0
Bank Sta=5002.8,5034.9
Exp/Cntr=0.3,0.1

Type RM Length L Ch R = 1,306500,500,500,500
BEGIN DESCRIPTION:
Sweetwater Creek 611.0
END DESCRIPTION:
XS GIS Cut Line= 3
      1367905.00      6794088.01      1367947.89      6793840.50
      1368354.99      6793488.00
#Sta/Elev= 30
  4748.8 2418.92  4850.3 2418.57  4901.0 2407.20  4955.3 2403.04  4956.0 2395.30
  4956.5 2394.80  4988.1 2395.30  4988.3 2395.39  4992.4 2397.15  5028.0 2398.67
  5049.1 2401.30  5113.5 2399.69  5127.8 2400.25  5134.4 2402.76  5139.3 2403.10
  5155.2 2407.68  5181.3 2407.79  5283.5 2406.82  5312.0 2407.78  5326.3 2409.97
  5340.1 2413.57  5368.0 2418.23  5389.9 2424.92  5418.4 2438.16  5432.6 2447.50
  5449.8 2457.00  5460.1 2463.09  5474.4 2466.13  5517.1 2467.48  5538.5 2466.79
#Mann=7,-1,0
  4748.8    0.07       0  4956.0    0.07       0  4988.1    0.07       0
  4988.3    0.16       0  5139.3    0.07       0  5181.3    0.16       0
  5449.8    0.07       0
Bank Sta=4956,4988.1
Exp/Cntr=0.3,0.1

Type RM Length L Ch R = 1,306000,500,500,500
BEGIN DESCRIPTION:
Sweetwater Creek 610.0
END DESCRIPTION:
XS GIS Cut Line= 3
      1368055.00      6794088.00      1368401.62      6793981.57
      1368504.98      6793788.04
#Sta/Elev= 30
  4637.4 2417.47  4659.0 2415.03  4668.8 2411.64  4700.2 2406.53  4757.2 2405.84
  4773.4 2405.05  4795.1 2401.25  4821.9 2401.65  4860.6 2403.15  4951.2 2400.69
  4972.1 2397.79  4991.5 2397.02  4996.7 2395.28  4997.6 2392.96  4998.2 2392.46
  5029.8 2392.96  5035.7 2394.69  5049.4 2395.52  5079.6 2403.95  5129.2 2411.64
  5145.5 2417.20  5151.4 2420.97  5161.7 2425.08  5174.1 2432.35  5183.7 2435.30
  5189.4 2439.92  5196.8 2443.71  5205.6 2445.71  5209.1 2445.50  5219.4 2446.01
#Mann=5,-1,0
  4637.4    0.07       0  4821.9    0.16       0  4997.6    0.07       0
  5029.8    0.16       0  5209.1    0.07       0
Bank Sta=4997.6,5029.8
Exp/Cntr=0.3,0.1

Type RM Length L Ch R = 1,305500,500,500,500
BEGIN DESCRIPTION:
Sweetwater Creek 609.0
END DESCRIPTION:
XS GIS Cut Line= 3
      1368004.98      6794238.00      1368525.29      6794288.00
      1368754.97      6794387.98
#Sta/Elev= 30
  4477.3 2417.82  4587.8 2417.12  4633.6 2413.96  4678.2 2412.51  4833.9 2409.66
  4838.6 2409.10  4843.6 2410.00  4889.2 2399.17  4919.3 2395.98  4929.4 2397.17
  4939.2 2395.10  4951.1 2393.94  4979.6 2396.40  4989.7 2394.80  4997.3 2391.20
  5002.6 2391.20  5003.6 2387.66  5004.4 2387.16  5039.5 2387.66  5043.3 2391.99
  5084.6 2393.10  5113.5 2396.40  5130.6 2413.14  5136.9 2428.38  5142.4 2430.80
  5152.4 2433.03  5174.2 2434.55  5206.9 2434.69  5241.5 2434.18  5250.5 2432.79
#Mann=5,-1,0
  4477.3    0.07       0  4833.9    0.16       0  4939.2    0.07       0
  5003.6    0.07       0  5039.5    0.07       0
Bank Sta=5003.6,5039.5
Exp/Cntr=0.3,0.1

Type RM Length L Ch R = 1,305000,500,500,500
BEGIN DESCRIPTION:
Sweetwater Creek 608.0
END DESCRIPTION:
XS GIS Cut Line= 3
      1368104.99      6794688.00      1368454.95      6794751.07
      1368705.02      6794687.99
#Sta/Elev= 30
  4644.4 2411.11  4664.7 2409.66  4676.3 2407.21  4685.1 2406.68  4847.6 2404.71
  4878.1 2401.19  4908.6 2399.76  4939.1 2391.59  4949.2 2390.89  4954.4 2388.12
  4959.5 2389.02  4969.6 2386.86  4971.9 2384.97  4972.7 2384.47  5007.8 2384.97
  5010.4 2388.37  5029.4 2391.90  5034.6 2391.58  5041.3 2392.90  5061.9 2392.88
  5075.6 2391.57  5111.6 2390.62  5116.7 2392.21  5152.6 2391.55  5157.8 2392.56
  5175.4 2392.94  5198.9 2395.95  5239.9 2405.97  5247.6 2407.41  5257.9 2408.09
#Mann=3,-1,0
  4644.4    0.07       0  4971.9    0.07       0  5007.8    0.16       0
Bank Sta=4971.9,5007.8
Exp/Cntr=0.3,0.1