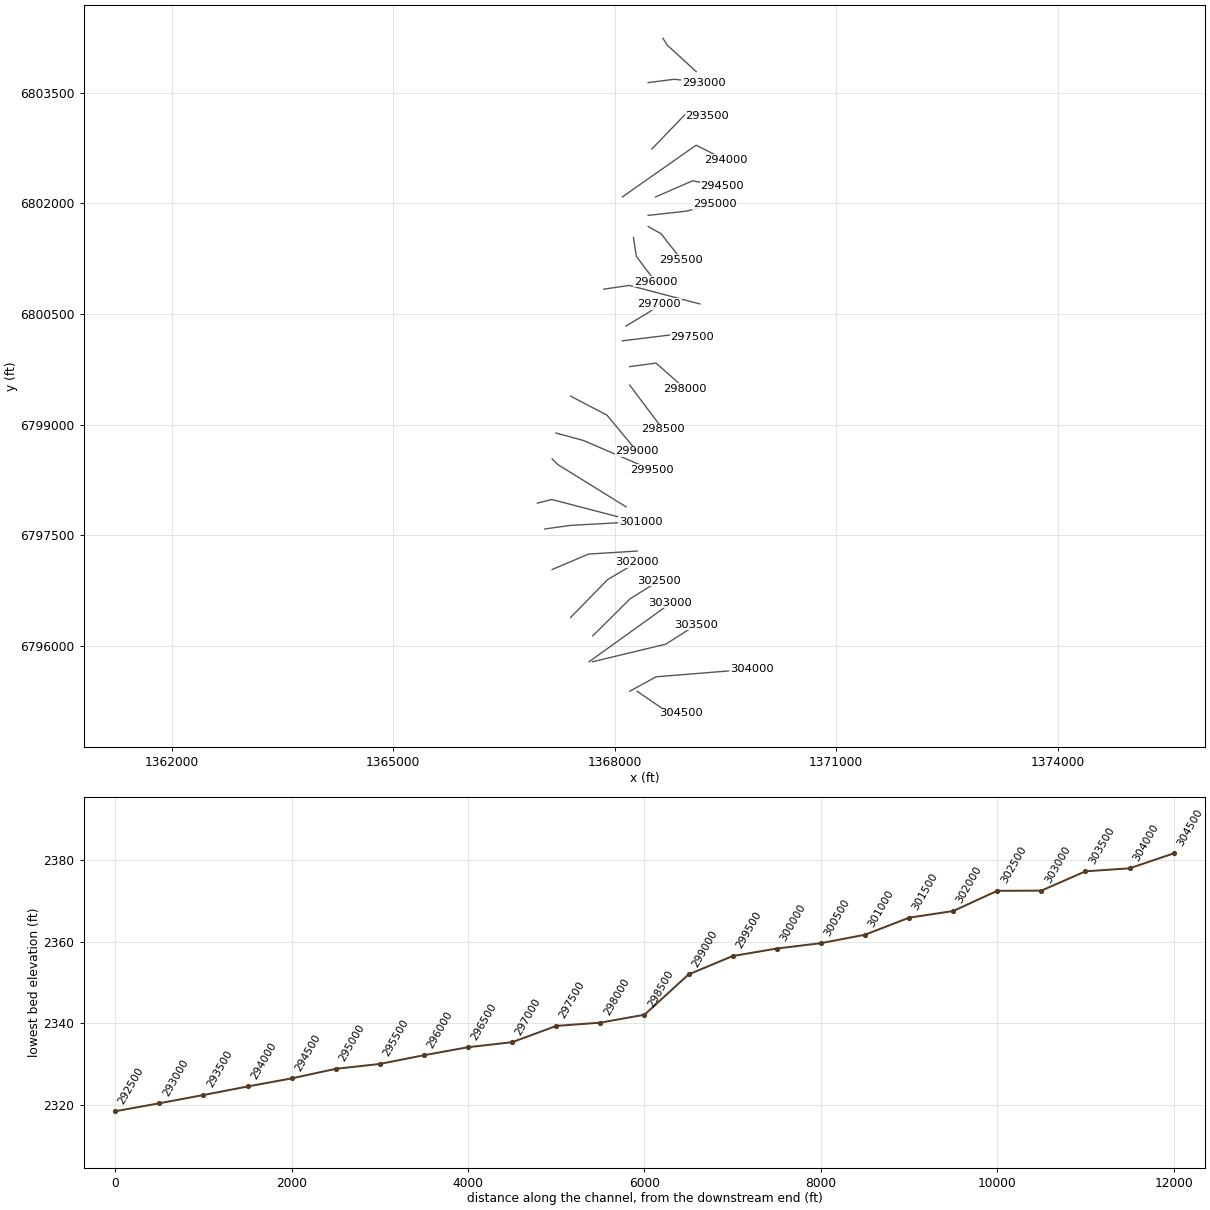
HEC-RAS study Sweetwater Creek.prj: Sweetwater Creek Base Level Engineering

--- Sweetwater Creek.g01 (geometry) --- (continued)

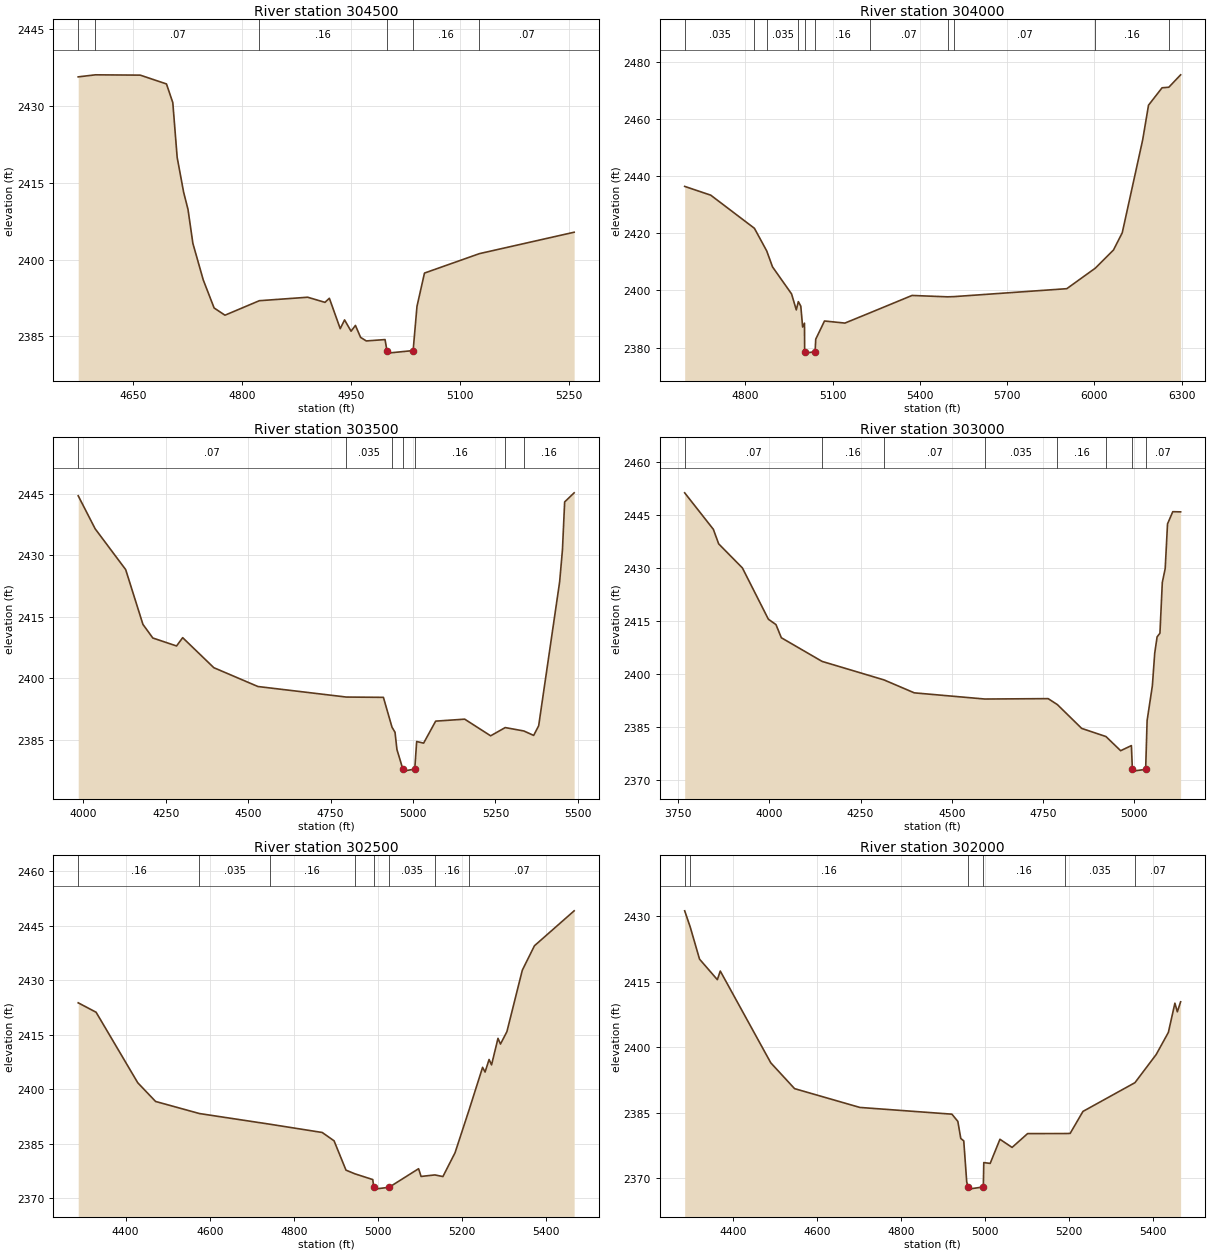
Type RM Length L Ch R = 1,304500,500,500,500
BEGIN DESCRIPTION:
Sweetwater Creek 607.0
END DESCRIPTION:
XS GIS Cut Line= 3
      1368305.00      6795388.00      1368655.46      6795147.58
      1368905.05      6795087.99
#Sta/Elev= 30
  4575.0 2435.69  4598.6 2436.09  4660.2 2436.03  4696.3 2434.31  4705.0 2430.66
  4711.0 2419.96  4719.9 2413.15  4725.9 2409.79  4732.6 2403.16  4746.9 2396.00
  4761.8 2390.54  4776.7 2389.13  4823.9 2391.96  4890.4 2392.64  4914.1 2391.64
  4920.2 2392.44  4935.1 2386.50  4941.1 2388.21  4950.0 2386.00  4956.0 2387.13
  4963.1 2384.80  4970.9 2384.10  4996.7 2384.37  4999.3 2382.22  5000.2 2381.72
  5035.3 2382.22  5040.6 2390.86  5050.9 2397.36  5126.5 2401.16  5256.6 2405.34
#Mann=6,-1,0
  4575.0   0.035       0  4598.6    0.07       0  4823.9    0.16       0
  4999.3    0.07       0  5035.3    0.16       0  5126.5    0.07       0
Bank Sta=4999.3,5035.3
Exp/Cntr=0.3,0.1

Type RM Length L Ch R = 1,304000,500,500,500
BEGIN DESCRIPTION:
Sweetwater Creek 606.0
END DESCRIPTION:
XS GIS Cut Line= 3
      1368204.97      6795387.98      1368563.05      6795584.15
      1369854.99      6795688.00
#Sta/Elev= 30
  4591.7 2436.43  4681.3 2433.36  4831.4 2421.76  4873.7 2413.83  4893.7 2408.23
  4959.1 2398.78  4975.3 2393.19  4982.3 2396.09  4990.8 2394.49  4997.1 2387.20
  5003.5 2388.54  5004.0 2378.56  5004.9 2378.06  5040.0 2378.56  5042.1 2382.93
  5072.2 2389.31  5142.4 2388.58  5229.0 2392.19  5373.1 2398.25  5495.3 2397.77
  5516.8 2397.84  5904.9 2400.62  6003.0 2407.81  6065.4 2414.17  6095.5 2420.19
  6165.7 2452.71  6185.8 2464.86  6232.3 2470.95  6255.6 2471.15  6296.1 2475.49
#Mann=11,-1,0
  4591.7   0.035       0  4831.4    0.07       0  4873.7   0.035       0
  4982.3    0.16       0  5004.0    0.07       0  5040.0    0.16       0
  5229.0    0.07       0  5495.3    0.16       0  5516.8    0.07       0
  6003.0    0.16       0  6255.6    0.07       0
Bank Sta=5004,5040
Exp/Cntr=0.3,0.1

Type RM Length L Ch R = 1,303500,500,500,500
BEGIN DESCRIPTION:
Sweetwater Creek 605.0
END DESCRIPTION:
XS GIS Cut Line= 3
      1367705.01      6795788.00      1368692.23      6796025.97
      1369104.99      6796287.99
#Sta/Elev= 30
  3984.5 2444.46  4035.9 2436.41  4128.5 2426.46  4180.8 2413.11  4210.8 2409.78
  4282.8 2407.84  4301.4 2409.86  4395.9 2402.54  4529.7 2397.95  4797.9 2395.38
  4910.3 2395.31  4936.3 2388.05  4945.5 2386.79  4951.4 2382.57  4969.3 2377.82
  4970.2 2377.32  5005.4 2377.82  5011.2 2384.54  5032.3 2384.15  5068.8 2389.51
  5156.9 2389.99  5235.6 2385.93  5279.8 2387.94  5336.3 2387.11  5366.1 2386.03
  5381.3 2388.39  5444.9 2423.48  5453.4 2431.27  5460.1 2442.96  5488.9 2445.18
#Mann=7,-1,0
  3984.5    0.07       0  4797.9   0.035       0  4936.3    0.16       0
  4969.3    0.07       0  5005.4    0.16       0  5279.8    0.07       0
  5336.3    0.16       0
Bank Sta=4969.3,5005.4
Exp/Cntr=0.3,0.1

Type RM Length L Ch R = 1,303000,500,500,500
BEGIN DESCRIPTION:
Sweetwater Creek 604.0
END DESCRIPTION:
XS GIS Cut Line= 3
      1367655.02      6795788.01      1368655.86      6796507.12
      1368754.97      6796587.97
#Sta/Elev= 30
  3767.6 2451.36  3846.2 2441.04  3860.9 2436.91  3925.9 2430.10  3997.2 2415.58
  4018.0 2414.06  4032.8 2410.33  4144.5 2403.64  4314.1 2398.41  4397.4 2394.74
  4590.8 2392.99  4764.5 2393.10  4789.8 2391.42  4856.6 2384.67  4923.1 2382.37
  4963.4 2378.36  4992.9 2379.81  4995.6 2373.08  4996.4 2372.58  5032.0 2373.08
  5036.0 2386.90  5050.4 2396.73  5056.9 2405.99  5063.4 2410.58  5071.2 2411.63
  5077.7 2426.01  5085.6 2429.90  5092.0 2442.57  5106.4 2446.02  5127.9 2445.97
#Mann=8,-1,0
  3767.6    0.07       0  4144.5    0.16       0  4314.1    0.07       0
  4590.8   0.035       0  4789.8    0.16       0  4923.1    0.07       0
  4995.6    0.07       0  5032.0    0.07       0
Bank Sta=4995.6,5032
Exp/Cntr=0.3,0.1

Type RM Length L Ch R = 1,302500,500,500,500
BEGIN DESCRIPTION:
Sweetwater Creek 603.0
END DESCRIPTION:
XS GIS Cut Line= 3
      1367704.97      6796137.97      1368209.81      6796640.76
      1368605.03      6796888.02
#Sta/Elev= 30
  4287.5 2423.81  4330.0 2421.22  4429.0 2401.81  4471.4 2396.66  4575.7 2393.33
  4742.9 2390.40  4867.4 2388.12  4895.6 2385.83  4923.9 2377.76  4944.9 2376.75
  4987.6 2375.16  4989.9 2373.03  4990.8 2372.53  5026.3 2373.03  5096.5 2378.15
  5102.4 2376.02  5135.1 2376.44  5154.3 2375.99  5183.1 2382.54  5216.8 2394.45
  5248.6 2406.05  5254.5 2404.76  5264.0 2408.21  5269.9 2406.73  5285.2 2414.03
  5291.1 2412.46  5306.4 2415.88  5343.0 2432.79  5371.8 2439.51  5466.2 2449.13
#Mann=8,-1,0
  4287.5    0.16       0  4575.7   0.035       0  4742.9    0.16       0
  4944.9   0.035       0  4989.9   0.035       0  5026.3   0.035       0
  5135.1    0.16       0  5216.8    0.07       0
Bank Sta=4989.9,5026.3
Exp/Cntr=0.3,0.1

Type RM Length L Ch R = 1,302000,500,500,500
BEGIN DESCRIPTION:
Sweetwater Creek 602.0
END DESCRIPTION:
XS GIS Cut Line= 3
      1367405.00      6796388.00      1367905.01      6796900.49
      1368305.01      6797138.00
#Sta/Elev= 30
  4284.0 2431.20  4297.1 2427.53  4319.4 2420.15  4361.8 2415.46  4368.8 2417.43
  4489.1 2396.44  4545.7 2390.54  4701.3 2386.24  4920.5 2384.70  4934.6 2383.05
  4941.6 2379.15  4948.7 2378.59  4955.7 2369.26  4958.7 2368.06  4959.6 2367.56
  4995.3 2368.06  4996.4 2373.63  5011.6 2373.44  5034.9 2378.96  5063.8 2377.10
  5100.8 2380.26  5189.0 2380.27  5202.1 2380.30  5232.6 2385.33  5356.4 2391.90
  5407.0 2398.34  5436.0 2403.39  5451.6 2410.08  5457.4 2408.11  5465.2 2410.39
#Mann=6,-1,0
  4284.0   0.063       0  4297.1    0.16       0  4958.7    0.07       0
  4995.3    0.16       0  5189.0   0.035       0  5356.4    0.07       0
Bank Sta=4958.7,4995.3
Exp/Cntr=0.3,0.1

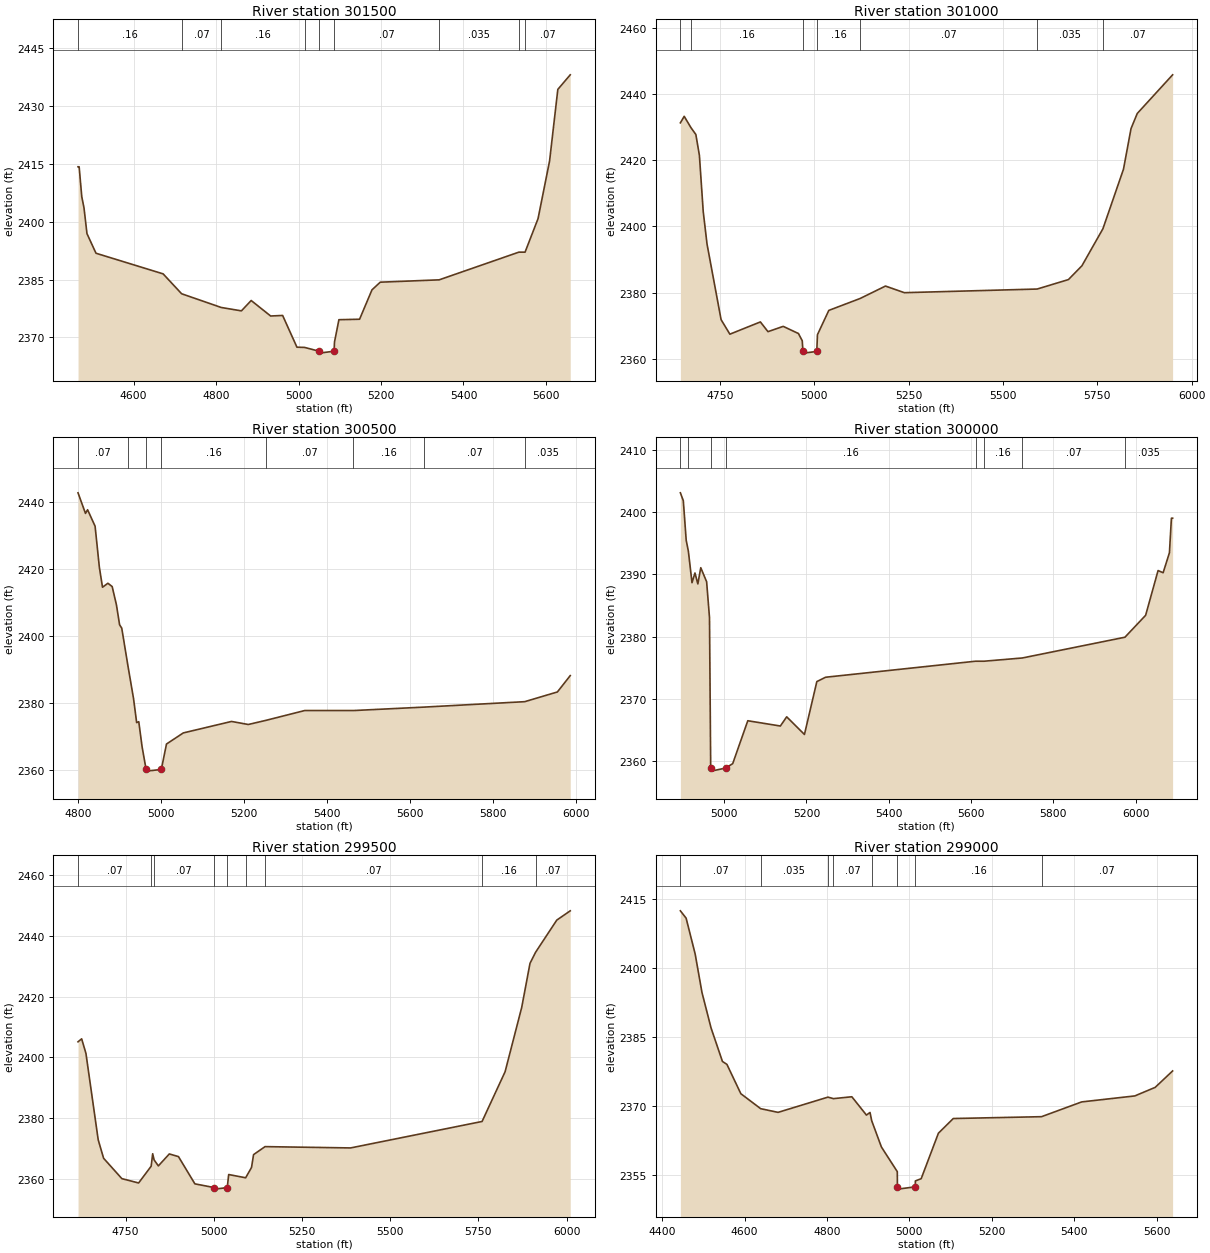
Type RM Length L Ch R = 1,301500,500,500,500
BEGIN DESCRIPTION:
Sweetwater Creek 601.0
END DESCRIPTION:
XS GIS Cut Line= 3
      1367155.02      6797038.01      1367647.26      6797247.35
      1368305.00      6797288.00
#Sta/Elev= 30
  4465.1 2414.27  4467.8 2414.27  4474.2 2406.50  4479.6 2403.61  4486.8 2396.93
  4508.7 2391.84  4671.5 2386.49  4716.4 2381.33  4812.5 2377.77  4861.4 2376.89
  4885.1 2379.58  4932.3 2375.56  4961.4 2375.70  4996.1 2367.47  5014.7 2367.41
  5049.6 2366.43  5050.5 2365.93  5086.2 2366.43  5087.2 2368.82  5097.9 2374.60
  5148.0 2374.72  5178.1 2382.34  5198.1 2384.33  5341.1 2384.94  5534.3 2392.12
  5549.4 2392.12  5580.9 2400.81  5608.9 2415.78  5628.9 2434.34  5659.0 2438.12
#Mann=9,-1,0
  4465.1    0.16       0  4716.4    0.07       0  4812.5    0.16       0
  5014.7    0.07       0  5049.6    0.07       0  5086.2    0.07       0
  5341.1   0.035       0  5534.3    0.16       0  5549.4    0.07       0
Bank Sta=5049.6,5086.2
Exp/Cntr=0.3,0.1

Type RM Length L Ch R = 1,301000,500,500,500
BEGIN DESCRIPTION:
Sweetwater Creek 600.0
END DESCRIPTION:
XS GIS Cut Line= 3
      1367055.02      6797588.00      1367406.89      6797636.54
      1368355.00      6797688.00
#Sta/Elev= 30
  4644.8 2431.27  4654.9 2433.24  4672.9 2429.80  4685.8 2427.75  4695.2 2421.44
  4705.3 2404.51  4715.4 2394.67  4752.7 2371.84  4776.0 2367.46  4856.8 2371.16
  4877.0 2368.22  4917.3 2369.82  4957.7 2367.66  4967.8 2365.47  4969.6 2362.24
  4970.5 2361.74  5006.3 2362.24  5008.1 2367.30  5038.2 2374.64  5121.3 2378.24
  5188.4 2381.99  5238.5 2379.99  5590.5 2381.09  5673.4 2383.95  5709.1 2388.11
  5764.8 2399.30  5819.3 2417.28  5839.3 2429.54  5855.8 2434.10  5949.5 2445.77
#Mann=7,-1,0
  4644.8    0.07       0  4672.9    0.16       0  4969.6    0.07       0
  5006.3    0.16       0  5121.3    0.07       0  5590.5   0.035       0
  5764.8    0.07       0
Bank Sta=4969.6,5006.3
Exp/Cntr=0.3,0.1

Type RM Length L Ch R = 1,300500,500,500,500
BEGIN DESCRIPTION:
Sweetwater Creek 599.0
END DESCRIPTION:
XS GIS Cut Line= 3
      1366955.05      6797938.01      1367149.62      6797986.82
      1368105.05      6797737.99
#Sta/Elev= 30
  4799.4 2442.74  4817.4 2436.60  4822.5 2437.69  4840.6 2432.78  4850.9 2420.51
  4858.5 2414.56  4871.5 2415.75  4881.8 2414.77  4892.1 2409.31  4899.7 2403.36
  4904.9 2402.36  4920.0 2390.99  4933.4 2381.31  4940.9 2374.15  4946.0 2374.43
  4954.0 2366.95  4963.7 2360.17  4964.6 2359.67  5000.4 2360.17  5012.9 2367.76
  5053.4 2371.07  5169.8 2374.50  5210.3 2373.59  5252.8 2374.82  5346.6 2377.76
  5463.9 2377.75  5634.5 2378.78  5877.4 2380.40  5956.3 2383.30  5987.3 2388.18
#Mann=8,-1,0
  4799.4    0.07       0  4920.0    0.16       0  4963.7    0.07       0
  5000.4    0.16       0  5252.8    0.07       0  5463.9    0.16       0
  5634.5    0.07       0  5877.4   0.035       0
Bank Sta=4963.7,5000.4
Exp/Cntr=0.3,0.1

Type RM Length L Ch R = 1,300000,500,500,500
BEGIN DESCRIPTION:
Sweetwater Creek 598.0
END DESCRIPTION:
XS GIS Cut Line= 3
      1367154.98      6798538.02      1367229.06      6798462.20
      1368154.97      6797888.02
#Sta/Elev= 30
  4894.0 2403.14  4901.1 2401.87  4908.1 2395.51  4913.4 2393.73  4922.2 2388.67
  4929.4 2390.24  4936.4 2388.48  4943.5 2391.09  4957.7 2388.83  4964.7 2383.04
  4967.6 2358.85  4968.5 2358.35  5004.3 2358.85  5021.1 2359.56  5057.7 2366.46
  5136.8 2365.61  5152.2 2367.09  5195.3 2364.25  5225.4 2372.76  5246.7 2373.46
  5611.0 2376.04  5631.6 2376.04  5724.5 2376.56  5973.7 2379.90  6024.0 2383.43
  6054.2 2390.63  6066.5 2390.28  6081.8 2393.50  6086.6 2399.06  6089.5 2399.06
#Mann=8,-1,0
  4894.0    0.07       0  4913.4    0.16       0  4967.6    0.07       0
  5004.3    0.16       0  5611.0    0.07       0  5631.6    0.16       0
  5724.5    0.07       0  5973.7   0.035       0
Bank Sta=4967.6,5004.3
Exp/Cntr=0.3,0.1

Type RM Length L Ch R = 1,299500,500,500,500
BEGIN DESCRIPTION:
Sweetwater Creek 597.0
END DESCRIPTION:
XS GIS Cut Line= 3
      1367205.02      6798887.99      1367576.83      6798787.67
      1368505.03      6798387.99
#Sta/Elev= 30
  4614.9 2405.07  4625.2 2406.06  4637.4 2401.22  4672.1 2372.78  4687.4 2366.69
  4739.2 2359.97  4786.7 2358.54  4822.3 2364.07  4826.6 2368.17  4830.6 2366.14
  4842.7 2364.17  4873.8 2368.11  4899.7 2367.23  4946.3 2358.25  5001.4 2357.01
  5002.3 2356.51  5038.1 2357.01  5042.1 2361.32  5090.2 2360.25  5106.9 2363.66
  5112.6 2367.88  5145.2 2370.52  5387.8 2370.09  5760.6 2378.81  5825.9 2395.21
  5873.0 2416.42  5896.5 2430.94  5912.4 2434.60  5972.5 2445.20  6010.6 2448.25
#Mann=9,-1,0
  4614.9    0.07       0  4822.3    0.16       0  4830.6    0.07       0
  5001.4    0.07       0  5038.1    0.07       0  5090.2    0.16       0
  5145.2    0.07       0  5760.6    0.16       0  5912.4    0.07       0
Bank Sta=5001.4,5038.1
Exp/Cntr=0.3,0.1

Type RM Length L Ch R = 1,299000,500,500,500
BEGIN DESCRIPTION:
Sweetwater Creek 596.0
END DESCRIPTION:
XS GIS Cut Line= 3
      1367404.97      6799388.02      1367897.38      6799130.02
      1368304.98      6798638.03
#Sta/Elev= 30
  4444.1 2412.46  4458.0 2410.87  4480.0 2403.06  4496.5 2394.71  4518.5 2387.02
  4546.2 2379.73  4557.0 2379.10  4590.9 2372.72  4639.0 2369.47  4681.2 2368.67
  4802.3 2371.98  4815.6 2371.65  4860.3 2372.06  4895.7 2368.08  4904.4 2368.65
  4908.5 2366.85  4932.1 2361.14  4970.6 2355.79  4970.9 2352.49  4971.9 2351.99
  5014.4 2352.49  5014.5 2353.77  5028.6 2354.26  5070.4 2364.14  5106.5 2367.33
  5320.7 2367.73  5418.2 2370.94  5547.1 2372.24  5596.6 2374.10  5638.9 2377.67
#Mann=8,-1,0
  4444.1    0.07       0  4639.0   0.035       0  4802.3    0.16       0
  4815.6    0.07       0  4908.5    0.16       0  4970.9    0.07       0
  5014.4    0.16       0  5320.7    0.07       0
Bank Sta=4970.9,5014.4
Exp/Cntr=0.3,0.1

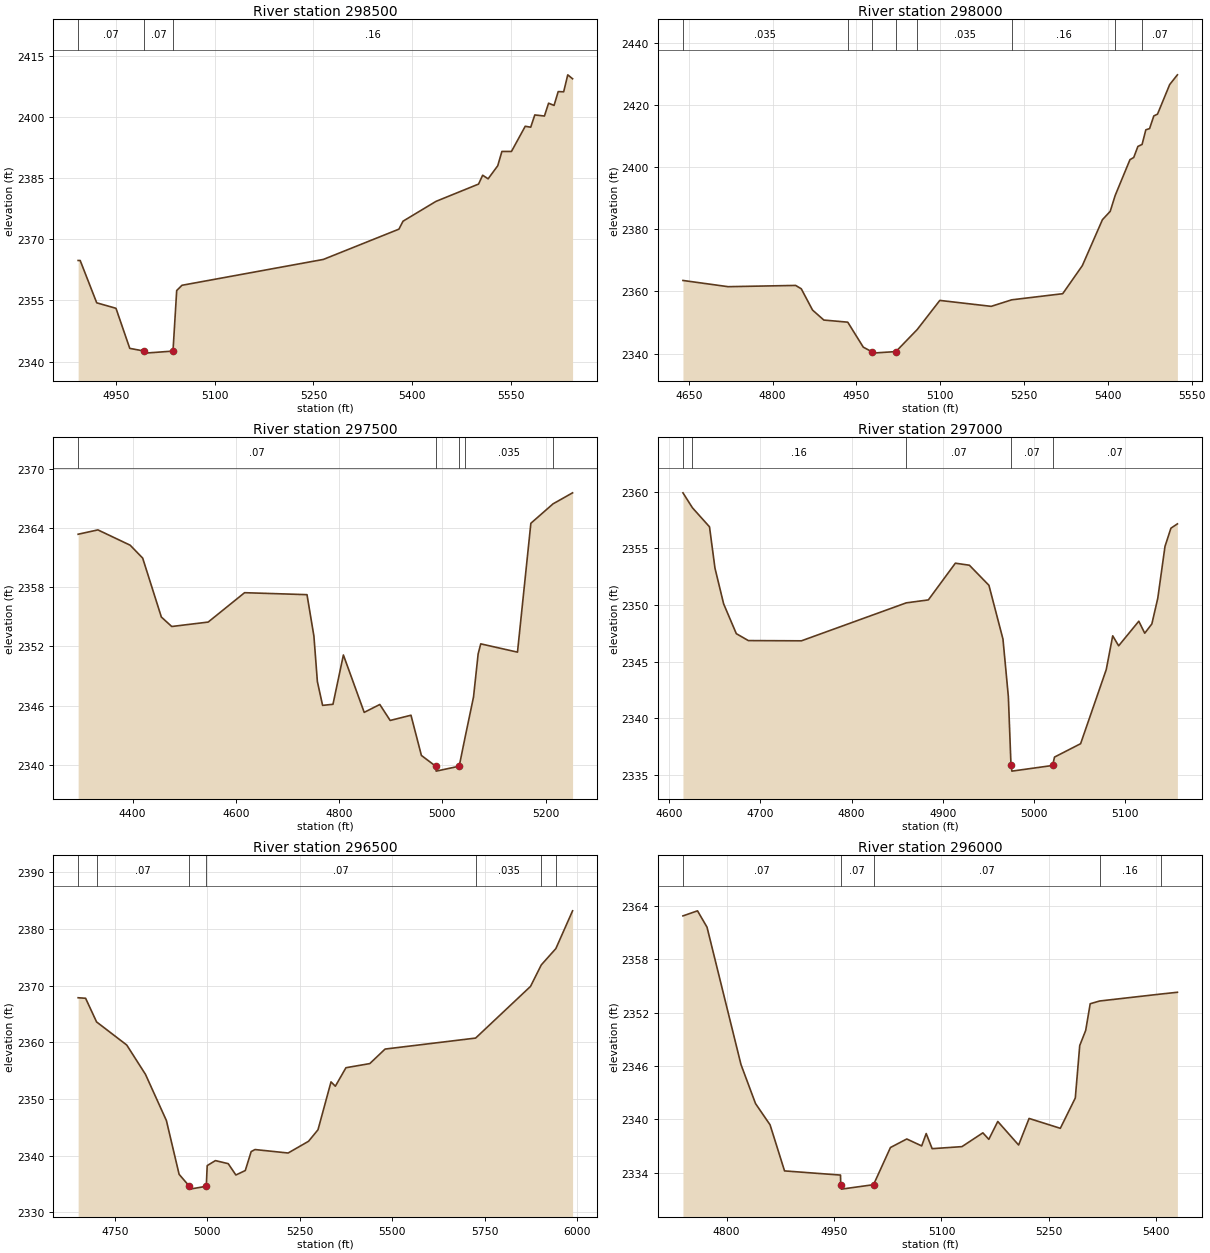
Type RM Length L Ch R = 1,298500,500,500,500
BEGIN DESCRIPTION:
Sweetwater Creek 595.0
END DESCRIPTION:
XS GIS Cut Line= 3
      1368204.99      6799538.01      1368268.62      6799451.99
      1368654.99      6798938.02
#Sta/Elev= 30
  4893.0 2364.80  4896.1 2364.80  4921.2 2354.42  4950.4 2353.08  4971.3 2343.26
  4993.3 2342.59  4994.3 2342.09  5036.9 2342.59  5042.5 2357.43  5050.5 2358.72
  5265.0 2365.06  5379.6 2372.48  5385.8 2374.43  5435.8 2379.29  5500.4 2383.53
  5506.6 2385.70  5514.9 2384.82  5529.5 2388.03  5535.8 2391.53  5550.3 2391.53
  5571.2 2397.70  5579.5 2397.47  5585.7 2400.48  5600.3 2400.21  5606.6 2403.36
  5614.9 2402.81  5621.2 2406.20  5629.5 2406.15  5635.7 2410.31  5643.0 2409.34
#Mann=3,-1,0
  4893.0    0.07       0  4993.3    0.07       0  5036.9    0.16       0
Bank Sta=4993.3,5036.9
Exp/Cntr=0.3,0.1

Type RM Length L Ch R = 1,298000,500,500,500
BEGIN DESCRIPTION:
Sweetwater Creek 594.0
END DESCRIPTION:
XS GIS Cut Line= 3
      1368205.04      6799788.01      1368562.45      6799835.85
      1368955.00      6799488.00
#Sta/Elev= 30
  4639.4 2363.53  4720.1 2361.53  4841.1 2361.93  4851.2 2360.85  4871.4 2354.00
  4891.6 2350.79  4934.4 2350.11  4962.2 2342.07  4977.0 2340.65  4978.0 2340.15
  5020.6 2340.65  5058.8 2347.75  5099.2 2357.11  5191.2 2355.20  5227.9 2357.30
  5319.2 2359.27  5354.3 2368.29  5390.3 2383.08  5404.2 2385.76  5413.1 2390.87
  5439.6 2402.40  5446.3 2403.09  5453.8 2406.65  5461.3 2407.30  5468.0 2412.00
  5474.7 2412.39  5482.3 2416.47  5488.9 2417.04  5510.7 2426.56  5524.5 2429.69
#Mann=8,-1,0
  4639.4   0.035       0  4934.4    0.07       0  4977.0    0.07       0
  5020.6    0.07       0  5058.8   0.035       0  5227.9    0.16       0
  5413.1   0.035       0  5461.3    0.07       0
Bank Sta=4977,5020.6
Exp/Cntr=0.3,0.1

Type RM Length L Ch R = 1,297500,500,500,500
BEGIN DESCRIPTION:
Sweetwater Creek 593.0
END DESCRIPTION:
XS GIS Cut Line= 3
      1368104.99      6800138.00      1368805.22      6800223.25
      1369055.05      6800187.99
#Sta/Elev= 30
  4294.6 2363.38  4332.9 2363.82  4395.3 2362.27  4419.6 2360.96  4455.8 2354.98
  4475.9 2354.02  4546.5 2354.47  4617.0 2357.45  4737.9 2357.25  4751.3 2353.04
  4758.0 2348.43  4768.1 2346.02  4788.2 2346.13  4808.4 2351.13  4848.7 2345.31
  4878.9 2346.11  4899.0 2344.49  4939.3 2345.02  4959.5 2340.94  4987.1 2339.85
  4988.1 2339.35  5032.7 2339.85  5043.5 2342.63  5060.4 2346.86  5069.4 2351.24
  5074.4 2352.26  5145.6 2351.42  5171.5 2364.49  5214.4 2366.46  5252.3 2367.58
#Mann=5,-1,0
  4294.6    0.07       0  4987.1    0.07       0  5032.7    0.07       0
  5043.5   0.035       0  5214.4    0.16       0
Bank Sta=4987.1,5032.7
Exp/Cntr=0.3,0.1

Type RM Length L Ch R = 1,297000,500,500,500
BEGIN DESCRIPTION:
Sweetwater Creek 592.0
END DESCRIPTION:
XS GIS Cut Line= 3
      1368155.02      6800338.01      1368484.05      6800537.53
      1368604.97      6800637.98
#Sta/Elev= 30
  4615.2 2359.91  4625.6 2358.59  4644.3 2356.91  4650.3 2353.26  4659.8 2350.11
  4673.7 2347.48  4686.9 2346.87  4745.1 2346.85  4860.0 2350.20  4884.2 2350.46
  4913.8 2353.70  4929.2 2353.52  4950.6 2351.75  4966.0 2347.00  4971.9 2341.92
  4974.8 2335.85  4975.8 2335.35  5020.4 2335.85  5022.5 2336.59  5051.1 2337.77
  5079.2 2344.31  5086.3 2347.29  5092.8 2346.41  5114.9 2348.58  5121.4 2347.52
  5129.2 2348.34  5135.7 2350.61  5143.6 2355.18  5150.1 2356.79  5157.2 2357.17
#Mann=5,-1,0
  4615.2    0.07       0  4625.6    0.16       0  4860.0    0.07       0
  4974.8    0.07       0  5020.4    0.07       0
Bank Sta=4974.8,5020.4
Exp/Cntr=0.3,0.1

Type RM Length L Ch R = 1,296500,500,500,500
BEGIN DESCRIPTION:
Sweetwater Creek 591.0
END DESCRIPTION:
XS GIS Cut Line= 3
      1367855.00      6800838.00      1368200.15      6800889.00
      1369155.01      6800638.00
#Sta/Elev= 30
  4651.1 2367.87  4671.3 2367.78  4700.9 2363.61  4782.5 2359.53  4833.1 2354.36
  4889.6 2346.22  4924.0 2336.73  4951.8 2334.62  4952.8 2334.12  4997.4 2334.62
  4999.9 2338.27  5022.1 2339.15  5056.7 2338.61  5077.4 2336.61  5102.8 2337.40
  5118.7 2340.74  5129.1 2341.10  5218.6 2340.49  5273.8 2342.56  5299.3 2344.59
  5334.5 2353.03  5346.2 2352.27  5374.8 2355.53  5439.3 2356.26  5480.6 2358.82
  5725.3 2360.76  5873.6 2369.87  5902.7 2373.66  5942.1 2376.54  5987.3 2383.20
#Mann=7,-1,0
  4651.1    0.16       0  4700.9    0.07       0  4951.8    0.07       0
  4997.4    0.07       0  5725.3   0.035       0  5902.7    0.16       0
  5942.1    0.07       0
Bank Sta=4951.8,4997.4
Exp/Cntr=0.3,0.1

Type RM Length L Ch R = 1,296000,500,500,500
BEGIN DESCRIPTION:
Sweetwater Creek 590.0
END DESCRIPTION:
XS GIS Cut Line= 3
      1368255.00      6801538.03      1368296.10      6801280.49
      1368554.98      6800938.03
#Sta/Elev= 30
  4739.2 2362.88  4759.5 2363.45  4772.8 2361.61  4820.2 2346.16  4840.5 2341.77
  4860.8 2339.38  4881.0 2334.20  4959.1 2333.73  4959.4 2332.65  4960.4 2332.15
  5005.2 2332.65  5028.8 2336.83  5051.6 2337.79  5072.4 2337.01  5078.7 2338.40
  5087.0 2336.70  5128.6 2336.93  5157.8 2338.48  5166.1 2337.75  5178.6 2339.76
  5207.7 2337.11  5222.3 2340.10  5265.9 2338.99  5286.8 2342.40  5293.0 2348.30
  5301.3 2350.00  5307.6 2353.00  5320.9 2353.31  5406.1 2354.09  5429.3 2354.29
#Mann=5,-1,0
  4739.2    0.07       0  4959.4    0.07       0  5005.2    0.07       0
  5320.9    0.16       0  5406.1    0.07       0
Bank Sta=4959.4,5005.2
Exp/Cntr=0.3,0.1

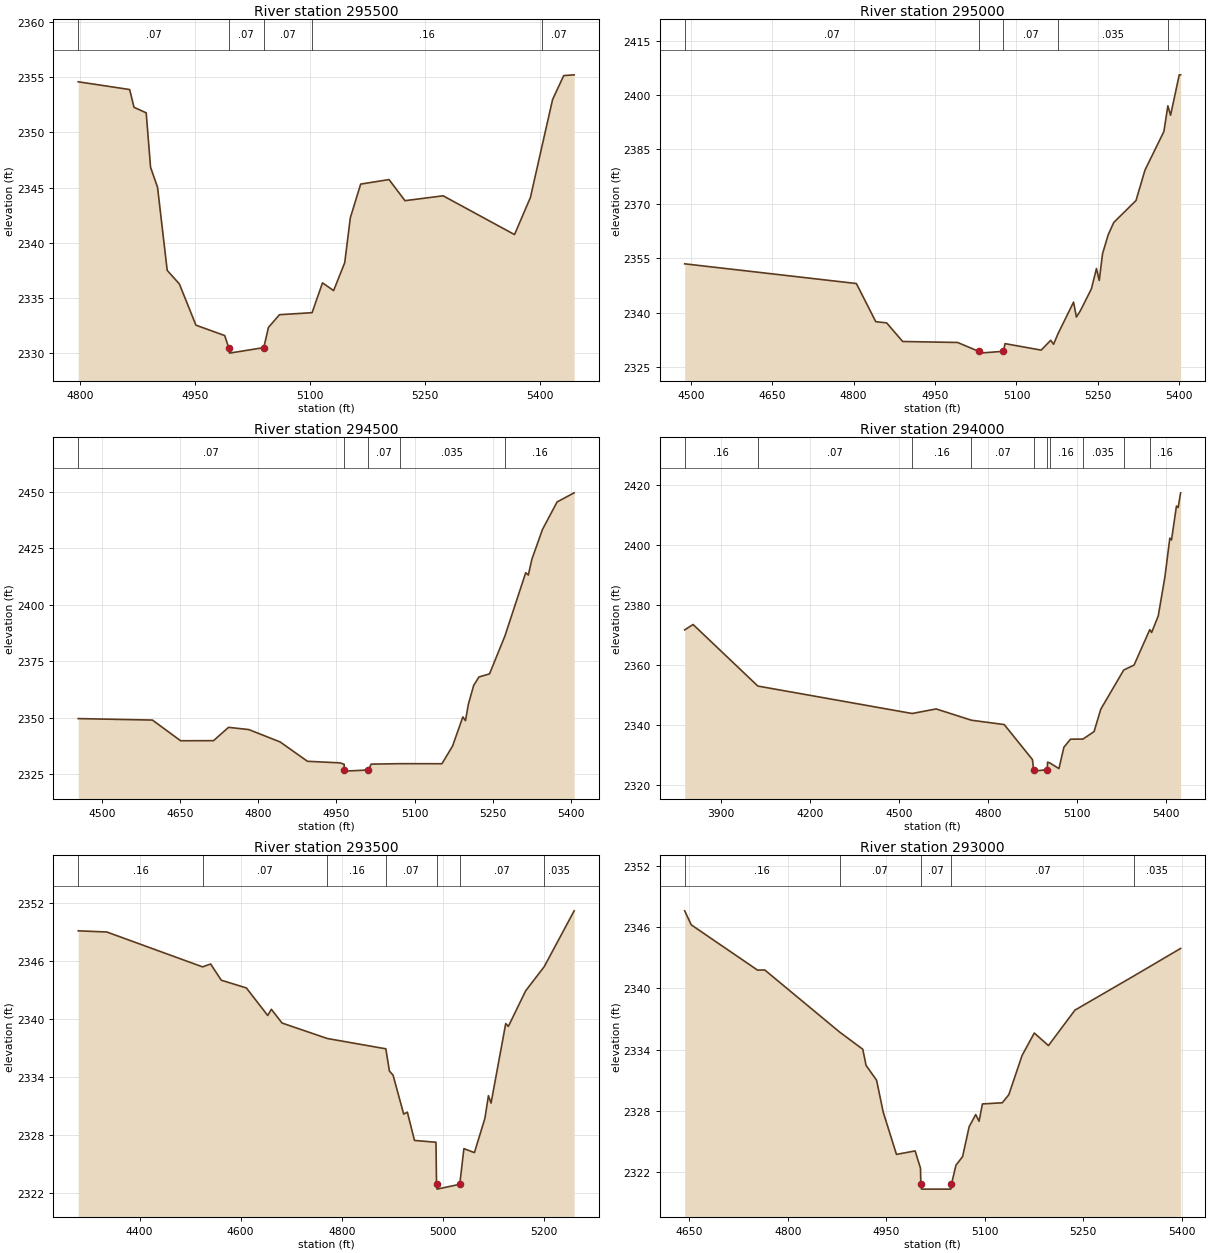
Type RM Length L Ch R = 1,295500,500,500,500
BEGIN DESCRIPTION:
Sweetwater Creek 589.0
END DESCRIPTION:
XS GIS Cut Line= 3
      1368455.02      6801687.99      1368631.24      6801588.03
      1368905.02      6801237.98
#Sta/Elev= 30
  4797.4 2354.57  4864.5 2353.87  4870.2 2352.26  4886.1 2351.76  4891.8 2346.83
  4900.9 2345.02  4913.5 2337.50  4929.4 2336.27  4951.0 2332.54  4988.5 2331.60
  4993.7 2330.51  4994.7 2330.01  5039.5 2330.51  5045.6 2332.34  5060.0 2333.49
  5102.5 2333.67  5116.1 2336.37  5130.6 2335.67  5145.1 2338.20  5152.4 2342.26
  5165.9 2345.31  5202.9 2345.72  5223.7 2343.81  5273.5 2344.25  5366.6 2340.74
  5387.4 2344.11  5403.1 2348.94  5416.3 2352.97  5430.8 2355.13  5444.4 2355.20
#Mann=5,-1,0
  4797.4    0.07       0  4993.7    0.07       0  5039.5    0.07       0
  5102.5    0.16       0  5403.1    0.07       0
Bank Sta=4993.7,5039.5
Exp/Cntr=0.3,0.1

Type RM Length L Ch R = 1,295000,500,500,500
BEGIN DESCRIPTION:
Sweetwater Creek 588.0
END DESCRIPTION:
XS GIS Cut Line= 3
      1368454.97      6801838.00      1368963.32      6801894.67
      1369354.96      6801987.99
#Sta/Elev= 30
  4488.5 2353.45  4805.0 2348.01  4840.7 2337.49  4860.8 2337.15  4890.3 2332.02
  4991.6 2331.75  5030.2 2329.31  5031.2 2328.81  5076.0 2329.31  5079.0 2331.43
  5145.6 2329.64  5163.2 2332.36  5168.4 2331.26  5177.0 2334.28  5205.3 2342.89
  5210.5 2338.76  5217.6 2340.44  5238.2 2346.55  5247.5 2352.16  5252.6 2348.86
  5258.7 2356.24  5269.0 2361.41  5279.3 2364.84  5320.4 2370.92  5336.9 2379.30
  5371.8 2389.96  5379.1 2397.04  5384.1 2394.45  5400.1 2405.59  5402.6 2405.59
#Mann=5,-1,0
  4488.5    0.07       0  5030.2    0.07       0  5076.0    0.07       0
  5177.0   0.035       0  5379.1    0.16       0
Bank Sta=5030.2,5076
Exp/Cntr=0.3,0.1

Type RM Length L Ch R = 1,294500,500,500,500
BEGIN DESCRIPTION:
Sweetwater Creek 587.0
END DESCRIPTION:
XS GIS Cut Line= 3
      1368555.02      6802088.01      1369054.73      6802306.02
      1369454.99      6802238.00
#Sta/Elev= 30
  4454.8 2349.67  4597.2 2349.02  4651.2 2339.88  4714.3 2339.92  4743.1 2345.81
  4782.1 2344.82  4842.2 2339.34  4894.5 2330.81  4956.7 2330.11  4964.8 2329.50
  4965.2 2326.96  4966.2 2326.46  5011.1 2326.96  5016.8 2329.56  5071.4 2329.75
  5152.4 2329.73  5172.7 2337.49  5192.5 2350.40  5197.6 2348.77  5203.1 2356.00
  5213.3 2364.34  5223.4 2368.07  5243.7 2369.43  5273.2 2386.17  5313.1 2414.14
  5318.1 2413.10  5324.9 2420.07  5345.2 2433.22  5373.3 2445.41  5406.0 2449.43
#Mann=5,-1,0
  4454.8    0.07       0  4965.2    0.07       0  5011.1    0.07       0
  5071.4   0.035       0  5273.2    0.16       0
Bank Sta=4965.2,5011.1
Exp/Cntr=0.3,0.1

Type RM Length L Ch R = 1,294000,500,500,500
BEGIN DESCRIPTION:
Sweetwater Creek 586.0
END DESCRIPTION:
XS GIS Cut Line= 3
      1368105.01      6802088.00      1369105.09      6802789.88
      1369505.02      6802587.99
#Sta/Elev= 30
  3778.2 2371.56  3806.5 2373.35  4024.5 2352.83  4544.0 2343.68  4624.9 2345.20
  4743.7 2341.44  4854.1 2339.99  4949.1 2328.32  4953.1 2324.97  4954.1 2324.47
  4999.0 2324.97  5000.0 2327.46  5006.6 2327.26  5038.3 2325.32  5055.0 2332.43
  5077.3 2335.12  5119.1 2335.15  5156.7 2337.66  5179.1 2345.09  5256.4 2358.17
  5291.2 2359.82  5344.1 2371.62  5350.4 2370.69  5372.7 2376.21  5395.0 2389.14
  5411.7 2402.14  5417.3 2401.52  5434.0 2412.83  5439.6 2412.34  5448.0 2417.24
#Mann=10,-1,0
  3778.2    0.16       0  4024.5    0.07       0  4544.0    0.16       0
  4743.7    0.07       0  4953.1    0.07       0  4999.0    0.07       0
  5006.6    0.16       0  5119.1   0.035       0  5256.4    0.07       0
  5344.1    0.16       0
Bank Sta=4953.1,4999
Exp/Cntr=0.3,0.1

Type RM Length L Ch R = 1,293500,500,500,500
BEGIN DESCRIPTION:
Sweetwater Creek 585.0
END DESCRIPTION:
XS GIS Cut Line= 3
      1368504.99      6802737.99      1369005.11      6803257.62
      1369255.00      6803188.00
#Sta/Elev= 30
  4278.8 2349.10  4335.3 2348.98  4524.7 2345.37  4540.6 2345.67  4561.7 2343.99
  4611.3 2343.19  4653.5 2340.34  4660.7 2340.98  4681.8 2339.56  4771.1 2337.96
  4887.1 2336.89  4894.1 2334.59  4901.3 2334.17  4922.4 2330.13  4929.6 2330.34
  4943.7 2327.41  4986.2 2327.22  4987.3 2322.87  4988.3 2322.37  5033.2 2322.87
  5041.4 2326.56  5062.2 2326.15  5082.9 2329.69  5089.9 2332.04  5095.1 2331.27
  5124.1 2339.50  5129.3 2339.21  5163.5 2342.89  5200.2 2345.39  5259.4 2351.17
#Mann=7,-1,0
  4278.8    0.16       0  4524.7    0.07       0  4771.1    0.16       0
  4887.1    0.07       0  4987.3    0.07       0  5033.2    0.07       0
  5200.2   0.035       0
Bank Sta=4987.3,5033.2
Exp/Cntr=0.3,0.1

Type RM Length L Ch R = 1,293000,500,500,500
BEGIN DESCRIPTION:
Sweetwater Creek 584.0
END DESCRIPTION:
XS GIS Cut Line= 3
      1368455.04      6803638.01      1368809.35      6803683.38
      1369204.96      6803638.00
#Sta/Elev= 30
  4642.8 2347.59  4652.8 2346.22  4753.7 2341.79  4764.8 2341.80  4878.9 2335.72
  4914.1 2334.04  4919.1 2332.46  4935.1 2331.01  4945.2 2327.89  4965.4 2323.75
  4993.8 2324.09  5002.0 2322.40  5002.5 2320.85  5003.5 2320.35  5048.2 2320.35
  5049.2 2320.85  5056.0 2322.69  5066.1 2323.53  5076.1 2326.46  5086.1 2327.65
  5091.2 2326.99  5096.3 2328.69  5126.5 2328.80  5136.5 2329.59  5156.7 2333.43
  5175.3 2335.63  5196.9 2334.40  5237.2 2337.87  5327.1 2341.22  5398.2 2343.91
#Mann=5,-1,0
  4642.8    0.16       0  4878.9    0.07       0  5002.5    0.07       0
  5049.2    0.07       0  5327.1   0.035       0
Bank Sta=5002.5,5049.2
Exp/Cntr=0.3,0.1

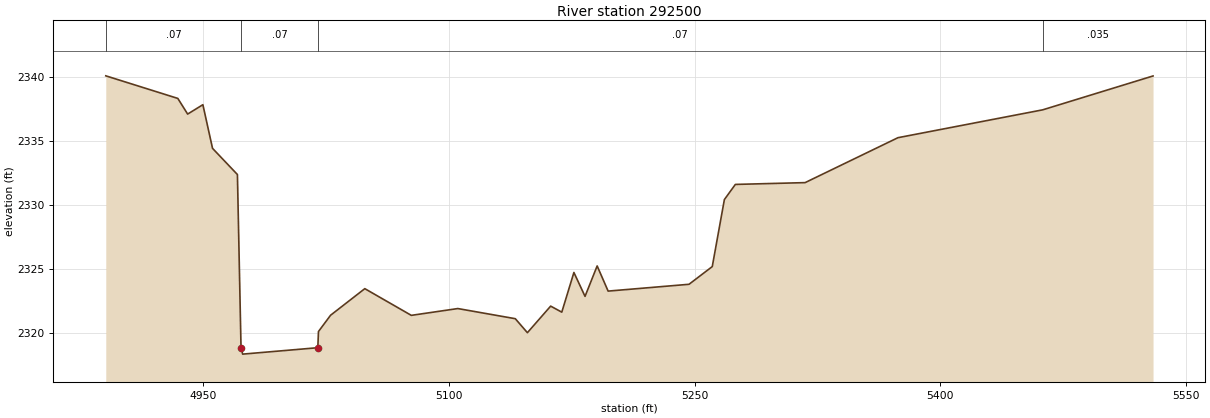
Type RM Length L Ch R = 1,292500,500,500,500
BEGIN DESCRIPTION:
Sweetwater Creek 583.0
END DESCRIPTION:
XS GIS Cut Line= 3
      1368654.98      6804238.02      1368713.86      6804145.58
      1369105.03      6803787.97
#Sta/Elev= 30
  4890.4 2340.07  4934.4 2338.31  4940.4 2337.09  4949.7 2337.82  4955.6 2334.42
  4970.8 2332.38  4973.0 2318.89  4974.0 2318.39  5019.9 2318.89  5020.3 2320.15
  5027.7 2321.42  5048.6 2323.49  5077.0 2321.41  5105.4 2321.94  5140.5 2321.15
  5147.9 2320.06  5162.1 2322.13  5168.9 2321.66  5176.3 2324.75  5183.1 2322.89
  5190.5 2325.26  5197.2 2323.30  5246.6 2323.83  5260.8 2325.21  5268.2 2330.43
  5274.9 2331.61  5317.5 2331.75  5374.2 2335.25  5462.6 2337.42  5530.0 2340.06
#Mann=4,-1,0
  4890.4    0.07       0  4973.0    0.07       0  5019.9    0.07       0
  5462.6   0.035       0
Bank Sta=4973,5019.9
Exp/Cntr=0.3,0.1