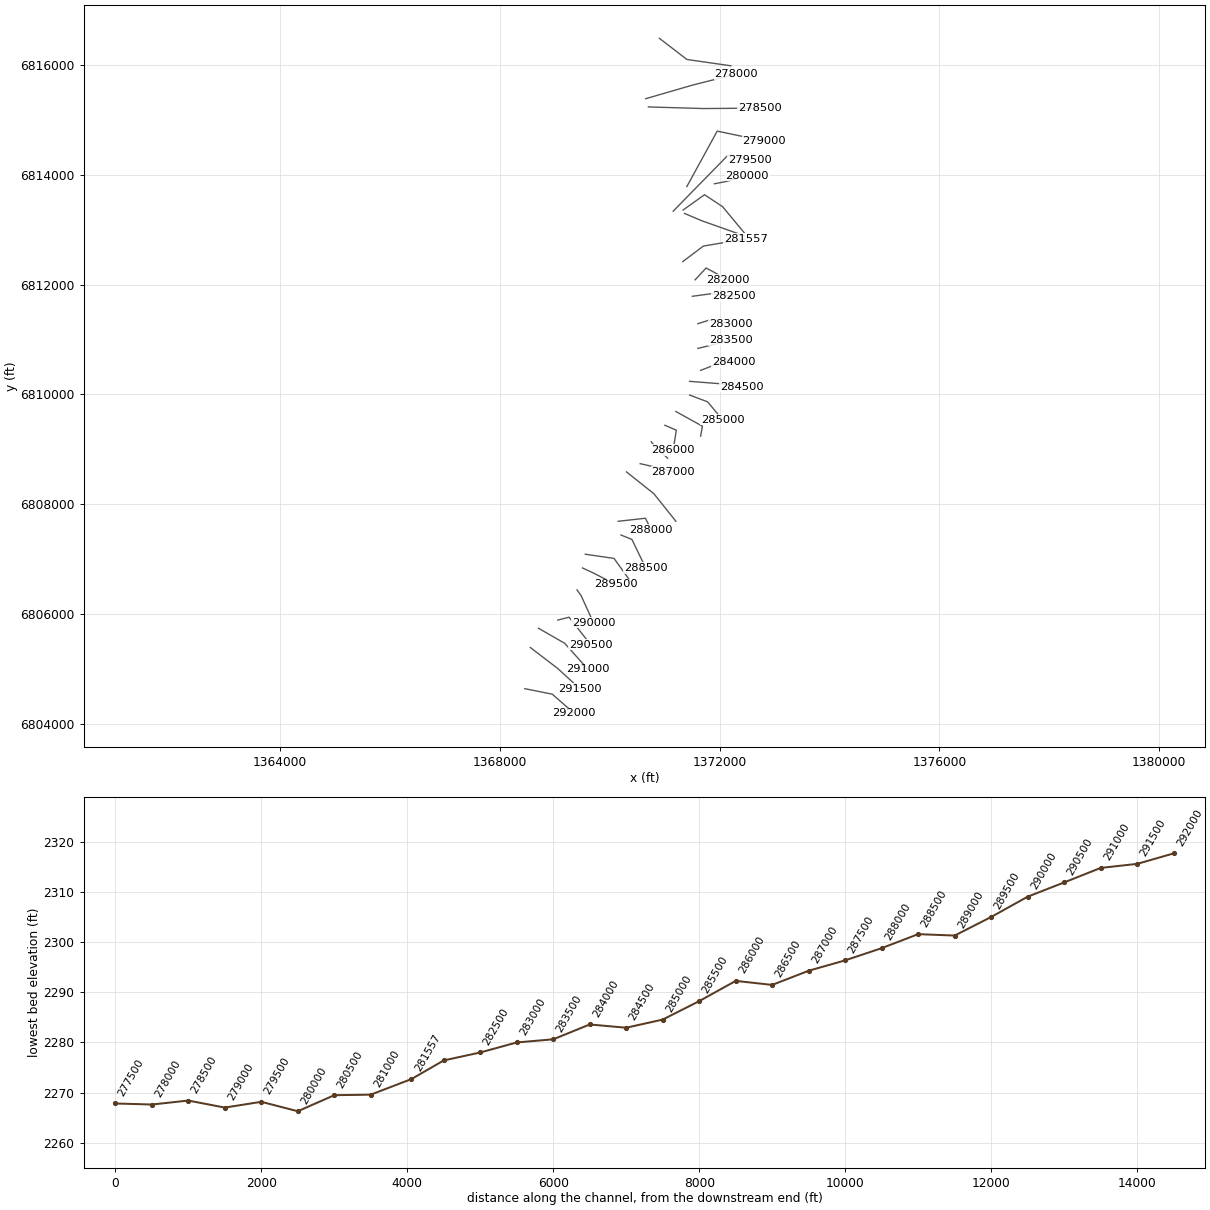
HEC-RAS study Sweetwater Creek.prj: Sweetwater Creek Base Level Engineering

--- Sweetwater Creek.g01 (geometry) --- (continued)

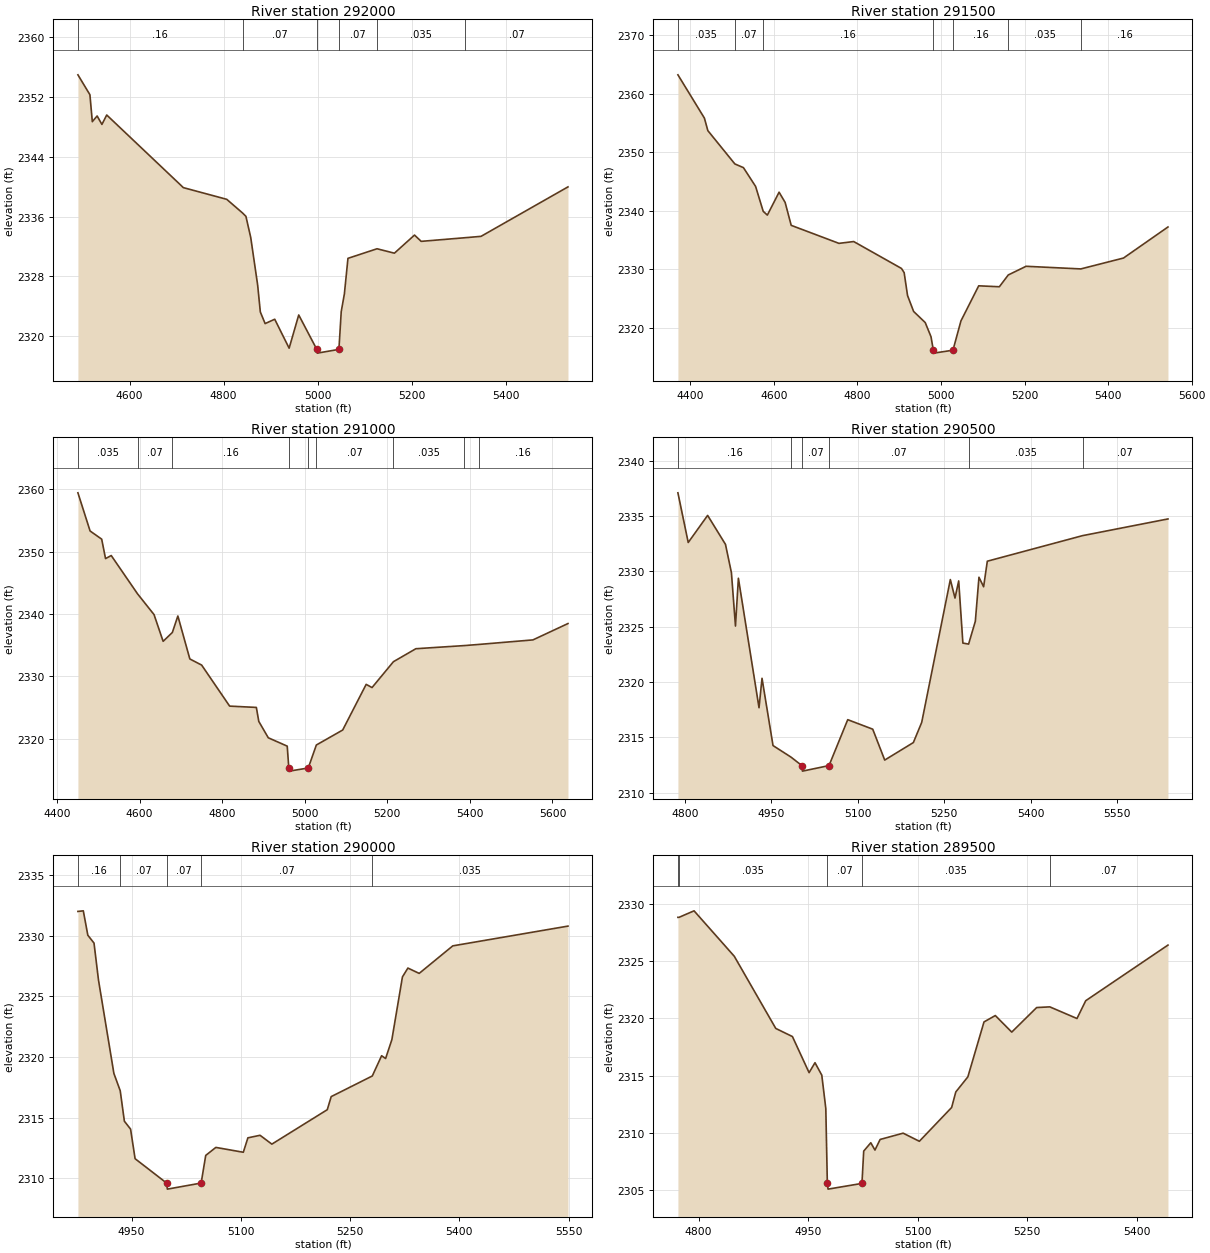
Type RM Length L Ch R = 1,292000,500,500,500
BEGIN DESCRIPTION:
Sweetwater Creek 582.0
END DESCRIPTION:
XS GIS Cut Line= 3
      1368454.96      6804638.01      1368954.70      6804537.74
      1369355.03      6804187.97
#Sta/Elev= 30
  4490.3 2354.94  4515.8 2352.28  4520.9 2348.68  4531.1 2349.44  4541.3 2348.31
  4551.5 2349.57  4714.4 2339.86  4806.5 2338.30  4840.2 2336.47  4847.3 2336.02
  4857.5 2333.20  4872.2 2326.85  4877.9 2323.24  4888.1 2321.69  4908.5 2322.27
  4939.1 2318.40  4959.5 2322.84  4997.9 2318.24  4998.9 2317.74  5044.9 2318.24
  5049.8 2323.29  5056.5 2325.66  5064.1 2330.41  5125.9 2331.69  5162.8 2331.10
  5205.5 2333.52  5219.7 2332.68  5313.5 2333.17  5346.9 2333.35  5531.6 2339.96
#Mann=6,-1,0
  4490.3    0.16       0  4840.2    0.07       0  4997.9    0.07       0
  5044.9    0.07       0  5125.9   0.035       0  5313.5    0.07       0
Bank Sta=4997.9,5044.9
Exp/Cntr=0.3,0.1

Type RM Length L Ch R = 1,291500,500,500,500
BEGIN DESCRIPTION:
Sweetwater Creek 581.0
END DESCRIPTION:
XS GIS Cut Line= 3
      1368555.01      6805387.99      1369054.89      6805005.54
      1369455.00      6804638.00
#Sta/Elev= 30
  4370.6 2363.24  4434.0 2355.84  4442.2 2353.70  4506.9 2348.00  4527.4 2347.37
  4556.5 2344.16  4574.7 2339.90  4584.6 2339.25  4612.7 2343.17  4627.2 2341.42
  4641.7 2337.50  4756.0 2334.42  4791.3 2334.73  4905.6 2330.13  4912.0 2329.41
  4920.1 2325.50  4934.6 2322.78  4962.4 2320.88  4976.3 2318.45  4981.8 2316.15
  4982.8 2315.65  5028.8 2316.15  5047.9 2321.16  5090.4 2327.16  5139.8 2327.00
  5161.2 2329.02  5203.8 2330.50  5334.8 2330.05  5436.9 2331.91  5543.3 2337.22
#Mann=7,-1,0
  4370.6   0.035       0  4506.9    0.07       0  4574.7    0.16       0
  4981.8    0.07       0  5028.8    0.16       0  5161.2   0.035       0
  5334.8    0.16       0
Bank Sta=4981.8,5028.8
Exp/Cntr=0.3,0.1

Type RM Length L Ch R = 1,291000,500,500,500
BEGIN DESCRIPTION:
Sweetwater Creek 580.0
END DESCRIPTION:
XS GIS Cut Line= 3
      1368705.01      6805737.99      1369181.59      6805464.65
      1369605.03      6804987.96
#Sta/Elev= 30
  4450.6 2359.40  4480.1 2353.29  4508.2 2351.98  4517.5 2348.87  4531.3 2349.36
  4595.0 2343.23  4635.0 2339.90  4657.0 2335.62  4679.3 2337.04  4692.7 2339.68
  4721.7 2332.80  4750.3 2331.82  4818.1 2325.25  4882.8 2325.04  4888.7 2322.80
  4911.7 2320.18  4957.6 2318.84  4961.4 2315.34  4962.4 2314.84  5008.5 2315.34
  5028.1 2319.02  5091.9 2321.42  5148.8 2328.73  5163.0 2328.22  5214.8 2332.36
  5269.2 2334.44  5386.4 2334.94  5420.9 2335.12  5552.7 2335.85  5637.6 2338.47
#Mann=9,-1,0
  4450.6   0.035       0  4595.0    0.07       0  4679.3    0.16       0
  4961.4    0.07       0  5008.5    0.16       0  5028.1    0.07       0
  5214.8   0.035       0  5386.4    0.07       0  5420.9    0.16       0
Bank Sta=4961.4,5008.5
Exp/Cntr=0.3,0.1

Type RM Length L Ch R = 1,290500,500,500,500
BEGIN DESCRIPTION:
Sweetwater Creek 579.0
END DESCRIPTION:
XS GIS Cut Line= 3
      1369054.98      6805887.99      1369260.66      6805940.18
      1369655.00      6805438.00
#Sta/Elev= 30
  4787.8 2337.10  4805.7 2332.61  4839.4 2335.06  4870.4 2332.44  4880.7 2329.88
  4887.7 2325.06  4892.8 2329.38  4928.6 2317.68  4933.8 2320.34  4952.9 2314.26
  4984.0 2313.22  5003.0 2312.45  5004.0 2311.95  5050.1 2312.45  5082.6 2316.60
  5126.0 2315.74  5146.8 2312.95  5196.5 2314.53  5211.0 2316.35  5260.7 2329.26
  5268.8 2327.59  5275.2 2329.14  5282.5 2323.52  5292.4 2323.43  5304.1 2325.49
  5310.4 2329.47  5318.5 2328.61  5324.9 2330.92  5490.2 2333.23  5638.5 2334.74
#Mann=6,-1,0
  4787.8    0.16       0  4984.0    0.07       0  5003.0    0.07       0
  5050.1    0.07       0  5292.4   0.035       0  5490.2    0.07       0
Bank Sta=5003,5050.1
Exp/Cntr=0.3,0.1

Type RM Length L Ch R = 1,290000,500,500,500
BEGIN DESCRIPTION:
Sweetwater Creek 578.0
END DESCRIPTION:
XS GIS Cut Line= 3
      1369404.98      6806438.03      1369477.53      6806337.83
      1369705.02      6805837.96
#Sta/Elev= 30
  4876.3 2332.00  4883.7 2332.05  4889.9 2330.04  4898.4 2329.39  4904.6 2326.32
  4925.7 2318.64  4934.4 2317.21  4940.1 2314.70  4948.6 2314.05  4954.8 2311.61
  4998.1 2309.60  4999.1 2309.10  5045.5 2309.60  5051.8 2311.88  5065.7 2312.54
  5103.4 2312.14  5109.7 2313.33  5126.4 2313.54  5142.6 2312.81  5218.7 2315.65
  5224.1 2316.73  5280.5 2318.43  5293.3 2320.10  5298.8 2319.87  5307.4 2321.43
  5321.9 2326.60  5329.4 2327.33  5344.9 2326.89  5391.0 2329.16  5549.2 2330.79
#Mann=5,-1,0
  4876.3    0.16       0  4934.4    0.07       0  4998.1    0.07       0
  5045.5    0.07       0  5280.5   0.035       0
Bank Sta=4998.1,5045.5
Exp/Cntr=0.3,0.1

Type RM Length L Ch R = 1,289500,500,500,500
BEGIN DESCRIPTION:
Sweetwater Creek 577.0
END DESCRIPTION:
XS GIS Cut Line= 3
      1369504.97      6806838.01      1369711.79      6806741.32
      1370105.03      6806537.99
#Sta/Elev= 30
  4771.7 2328.85  4773.2 2328.85  4793.8 2329.42  4848.9 2325.44  4905.7 2319.12
  4928.5 2318.41  4951.3 2315.25  4959.4 2316.12  4968.7 2315.03  4974.2 2312.11
  4976.3 2305.55  4977.3 2305.05  5023.7 2305.55  5026.1 2308.38  5035.8 2309.11
  5041.5 2308.47  5048.6 2309.40  5080.1 2309.95  5102.3 2309.24  5146.5 2312.20
  5152.2 2313.56  5168.7 2314.88  5190.8 2319.69  5206.3 2320.25  5228.8 2318.80
  5262.9 2320.95  5280.9 2321.01  5318.1 2319.99  5330.1 2321.55  5442.7 2326.42
#Mann=5,-1,0
  4771.7    0.07       0  4773.2   0.035       0  4976.3    0.07       0
  5023.7   0.035       0  5280.9    0.07       0
Bank Sta=4976.3,5023.7
Exp/Cntr=0.3,0.1

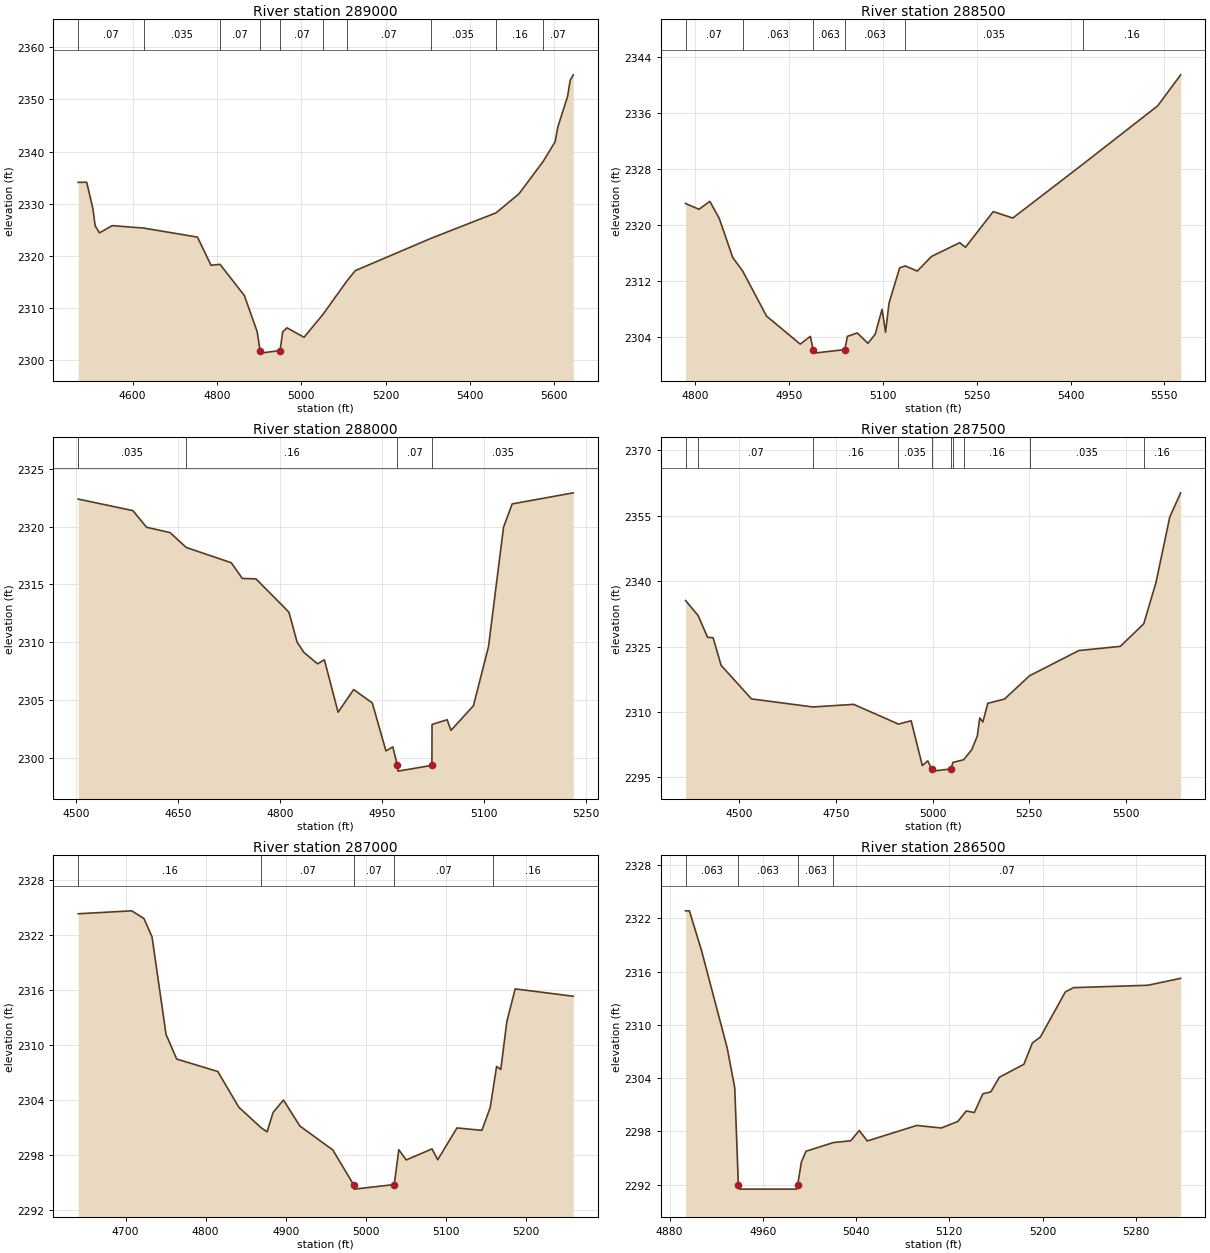
Type RM Length L Ch R = 1,289000,500,500,500
BEGIN DESCRIPTION:
Sweetwater Creek 576.0
END DESCRIPTION:
XS GIS Cut Line= 3
      1369555.05      6807087.99      1370078.70      6807011.59
      1370455.01      6806487.98
#Sta/Elev= 30
  4470.8 2334.09  4491.0 2334.11  4505.8 2329.03  4511.2 2325.73  4521.3 2324.41
  4551.6 2325.79  4626.1 2325.32  4753.7 2323.59  4785.8 2318.19  4807.2 2318.37
  4864.9 2312.38  4895.2 2305.47  4902.1 2301.84  4903.1 2301.34  4949.5 2301.84
  4955.8 2305.41  4965.9 2306.19  5006.4 2304.38  5051.2 2308.77  5108.9 2315.27
  5127.9 2317.16  5306.8 2323.33  5461.8 2328.25  5515.9 2331.88  5573.6 2338.13
  5601.8 2341.88  5608.0 2344.67  5631.3 2350.59  5637.4 2353.65  5644.8 2354.71
#Mann=10,-1,0
  4470.8    0.07       0  4626.1   0.035       0  4807.2    0.07       0
  4902.1    0.07       0  4949.5    0.07       0  5051.2    0.16       0
  5108.9    0.07       0  5306.8   0.035       0  5461.8    0.16       0
  5573.6    0.07       0
Bank Sta=4902.1,4949.5
Exp/Cntr=0.3,0.1

Type RM Length L Ch R = 1,288500,500,500,500
BEGIN DESCRIPTION:
Sweetwater Creek 575.0
END DESCRIPTION:
XS GIS Cut Line= 3
      1370205.02      6807437.99      1370404.80      6807356.94
      1370655.00      6806838.01
#Sta/Elev= 30
  4784.4 2323.05  4806.0 2322.22  4823.2 2323.36  4838.3 2320.92  4859.9 2315.31
  4875.5 2313.42  4913.9 2306.93  4967.8 2302.91  4984.0 2304.02  4988.4 2302.12
  4989.4 2301.62  5039.1 2302.12  5043.2 2304.02  5059.0 2304.51  5076.0 2303.03
  5087.6 2304.31  5098.6 2307.89  5104.2 2304.62  5109.8 2308.79  5126.8 2313.84
  5135.8 2314.11  5155.0 2313.37  5177.6 2315.46  5222.8 2317.44  5232.0 2316.78
  5276.4 2321.89  5307.7 2320.97  5419.2 2328.64  5539.4 2337.04  5576.1 2341.48
#Mann=6,-1,0
  4784.4    0.07       0  4875.5   0.063       0  4988.4   0.063       0
  5039.1   0.063       0  5135.8   0.035       0  5419.2    0.16       0
Bank Sta=4988.4,5039.1
Exp/Cntr=0.3,0.1

Type RM Length L Ch R = 1,288000,500,500,500
BEGIN DESCRIPTION:
Sweetwater Creek 574.0
END DESCRIPTION:
XS GIS Cut Line= 3
      1370155.03      6807688.00      1370649.22      6807743.51
      1370754.98      6807538.03
#Sta/Elev= 30
  4502.7 2322.38  4583.2 2321.38  4603.3 2319.94  4637.8 2319.48  4661.7 2318.19
  4727.9 2316.87  4744.2 2315.51  4764.3 2315.47  4804.6 2313.08  4812.9 2312.57
  4824.7 2310.01  4834.7 2309.11  4854.9 2308.12  4864.9 2308.47  4885.1 2303.93
  4908.0 2305.89  4935.4 2304.73  4955.5 2300.58  4965.6 2300.93  4972.3 2299.33
  4973.3 2298.83  5023.1 2299.33  5023.3 2302.87  5045.5 2303.28  5051.2 2302.36
  5084.2 2304.49  5106.4 2309.62  5128.5 2319.95  5141.2 2321.96  5231.1 2322.92
#Mann=4,-1,0
  4502.7   0.035       0  4661.7    0.16       0  4972.3    0.07       0
  5023.1   0.035       0
Bank Sta=4972.3,5023.1
Exp/Cntr=0.3,0.1

Type RM Length L Ch R = 1,287500,500,500,500
BEGIN DESCRIPTION:
Sweetwater Creek 573.0
END DESCRIPTION:
XS GIS Cut Line= 3
      1370305.00      6808588.00      1370805.08      6808189.41
      1371205.02      6807687.97
#Sta/Elev= 30
  4360.5 2335.56  4393.1 2332.10  4417.4 2327.12  4431.8 2327.01  4452.6 2320.67
  4531.1 2312.97  4690.0 2311.12  4795.3 2311.72  4911.3 2307.19  4944.2 2307.95
  4973.1 2297.65  4987.1 2298.75  4997.1 2296.89  4998.1 2296.39  5047.9 2296.89
  5051.9 2298.38  5079.9 2299.00  5100.9 2301.30  5115.3 2304.45  5121.7 2308.60
  5129.7 2307.67  5142.5 2311.96  5185.8 2312.94  5250.4 2318.28  5377.9 2324.07
  5485.2 2325.03  5545.9 2330.20  5577.4 2339.63  5613.3 2354.74  5641.4 2360.28
#Mann=10,-1,0
  4360.5   0.063       0  4393.1    0.07       0  4690.0    0.16       0
  4911.3   0.035       0  4997.1   0.035       0  5047.9   0.035       0
  5051.9    0.07       0  5079.9    0.16       0  5250.4   0.035       0
  5545.9    0.16       0
Bank Sta=4997.1,5047.9
Exp/Cntr=0.3,0.1

Type RM Length L Ch R = 1,287000,500,500,500
BEGIN DESCRIPTION:
Sweetwater Creek 572.0
END DESCRIPTION:
XS GIS Cut Line= 3
      1370554.99      6808738.00      1370905.20      6808657.67
      1371154.97      6808588.01
#Sta/Elev= 30
  4640.7 2324.30  4707.6 2324.62  4722.8 2323.79  4733.0 2321.78  4750.5 2311.16
  4763.8 2308.48  4815.1 2307.13  4841.4 2303.24  4869.3 2301.00  4876.7 2300.56
  4884.3 2302.68  4897.2 2304.02  4917.7 2301.19  4958.8 2298.59  4984.7 2294.82
  4985.7 2294.32  5035.6 2294.82  5041.3 2298.61  5050.6 2297.50  5082.8 2298.70
  5089.9 2297.52  5114.0 2300.98  5145.1 2300.72  5155.5 2303.21  5158.9 2305.11
  5163.5 2307.68  5168.7 2307.35  5176.3 2312.57  5186.7 2316.12  5259.3 2315.32
#Mann=5,-1,0
  4640.7    0.16       0  4869.3    0.07       0  4984.7    0.07       0
  5035.6    0.07       0  5158.9    0.16       0
Bank Sta=4984.7,5035.6
Exp/Cntr=0.3,0.1

Type RM Length L Ch R = 1,286500,500,500,500
BEGIN DESCRIPTION:
Sweetwater Creek 571.0
END DESCRIPTION:
XS GIS Cut Line= 3
      1370755.01      6809137.98      1370823.95      6809057.06
      1371055.01      6808837.99
#Sta/Elev= 30
  4893.7 2322.86  4897.0 2322.86  4907.4 2318.39  4929.4 2307.42  4935.9 2302.92
  4939.0 2291.99  4940.0 2291.49  4988.9 2291.49  4989.9 2291.99  4993.1 2294.56
  4997.0 2295.76  5020.5 2296.74  5035.4 2296.94  5042.7 2298.10  5049.6 2296.92
  5092.1 2298.67  5113.1 2298.38  5127.3 2299.12  5134.5 2300.30  5141.4 2300.12
  5148.7 2302.23  5155.6 2302.46  5162.9 2304.10  5183.9 2305.56  5191.2 2307.96
  5198.1 2308.64  5219.5 2313.72  5226.4 2314.20  5290.3 2314.47  5318.4 2315.25
#Mann=4,-1,0
  4893.7   0.063       0  4939.0   0.063       0  4989.9   0.063       0
  5020.5    0.07       0
Bank Sta=4939,4989.9
Exp/Cntr=0.3,0.1

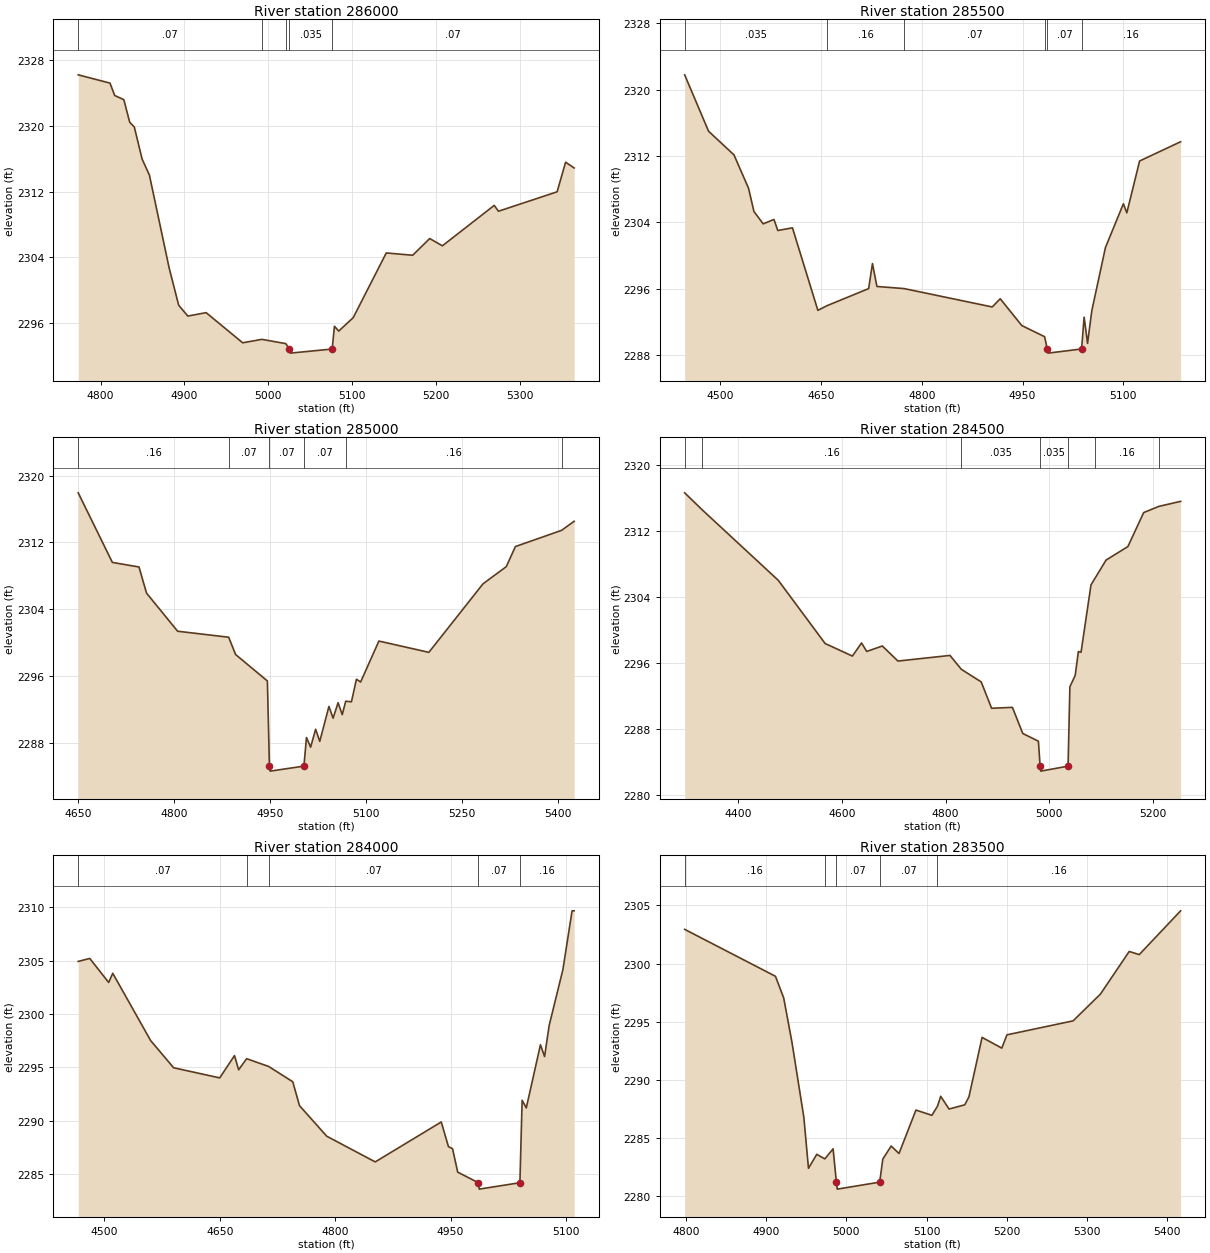
Type RM Length L Ch R = 1,286000,500,500,500
BEGIN DESCRIPTION:
Sweetwater Creek 570.0
END DESCRIPTION:
XS GIS Cut Line= 3
      1371005.04      6809437.98      1371213.02      6809348.03
      1371155.00      6808987.97
#Sta/Elev= 30
  4773.4 2326.24  4811.3 2325.23  4816.9 2323.72  4827.8 2323.21  4834.8 2320.46
  4840.3 2319.87  4849.6 2315.96  4858.3 2314.01  4881.8 2302.69  4893.2 2298.13
  4904.1 2296.81  4925.9 2297.23  4969.5 2293.55  4992.4 2293.97  5020.9 2293.45
  5025.2 2292.79  5026.2 2292.29  5076.2 2292.79  5078.9 2295.57  5084.0 2294.98
  5101.3 2296.62  5140.7 2304.51  5172.2 2304.23  5192.5 2306.27  5207.6 2305.38
  5269.4 2310.31  5274.5 2309.60  5344.4 2311.97  5354.5 2315.58  5364.7 2314.88
#Mann=5,-1,0
  4773.4    0.07       0  4992.4   0.035       0  5020.9    0.07       0
  5025.2   0.035       0  5076.2    0.07       0
Bank Sta=5025.2,5076.2
Exp/Cntr=0.3,0.1

Type RM Length L Ch R = 1,285500,500,500,500
BEGIN DESCRIPTION:
Sweetwater Creek 569.0
END DESCRIPTION:
XS GIS Cut Line= 3
      1371204.96      6809688.02      1371688.16      6809420.11
      1371655.00      6809238.01
#Sta/Elev= 30
  4447.5 2321.77  4483.0 2314.98  4520.8 2312.13  4542.5 2308.11  4550.5 2305.31
  4564.3 2303.82  4580.3 2304.35  4586.0 2303.02  4607.8 2303.34  4645.6 2293.40
  4659.1 2293.96  4721.1 2296.02  4726.8 2299.04  4733.4 2296.28  4774.1 2296.02
  4904.9 2293.81  4916.8 2294.80  4948.9 2291.57  4982.8 2290.23  4986.8 2288.75
  4987.8 2288.25  5037.8 2288.75  5041.6 2292.58  5046.7 2289.43  5053.0 2293.35
  5073.3 2300.97  5100.0 2306.24  5105.1 2305.15  5124.1 2311.39  5185.1 2313.71
#Mann=6,-1,0
  4447.5   0.035       0  4659.1    0.16       0  4774.1    0.07       0
  4982.8    0.16       0  4986.8    0.07       0  5037.8    0.16       0
Bank Sta=4986.8,5037.8
Exp/Cntr=0.3,0.1

Type RM Length L Ch R = 1,285000,500,500,500
BEGIN DESCRIPTION:
Sweetwater Creek 568.0
END DESCRIPTION:
XS GIS Cut Line= 3
      1371455.04      6809987.99      1371782.14      6809864.61
      1372055.01      6809537.99
#Sta/Elev= 30
  4650.4 2317.93  4703.8 2309.59  4745.4 2309.04  4757.2 2305.91  4805.8 2301.34
  4885.6 2300.62  4896.4 2298.55  4946.1 2295.38  4949.3 2285.17  4950.4 2284.57
  5003.2 2285.17  5007.2 2288.60  5013.7 2287.44  5021.5 2289.59  5028.0 2288.14
  5042.3 2292.33  5048.8 2290.92  5056.6 2292.77  5063.1 2291.34  5068.5 2292.95
  5077.5 2292.88  5085.3 2295.59  5091.8 2295.25  5120.4 2300.16  5198.5 2298.81
  5283.1 2307.02  5319.5 2309.08  5333.8 2311.49  5405.9 2313.43  5425.6 2314.52
#Mann=6,-1,0
  4650.4    0.16       0  4885.6    0.07       0  4949.3    0.07       0
  5003.2    0.07       0  5068.5    0.16       0  5405.9    0.07       0
Bank Sta=4949.3,5003.2
Exp/Cntr=0.3,0.1

Type RM Length L Ch R = 1,284500,500,500,500
BEGIN DESCRIPTION:
Sweetwater Creek 567.0
END DESCRIPTION:
XS GIS Cut Line= 3
      1371455.05      6810238.00      1372155.81      6810183.24
      1372405.04      6810137.99
#Sta/Elev= 30
  4297.1 2316.59  4330.1 2314.58  4477.6 2306.01  4567.9 2298.37  4620.5 2296.85
  4638.1 2298.44  4648.1 2297.41  4678.2 2298.07  4708.3 2296.25  4808.6 2296.93
  4830.5 2295.25  4868.8 2293.73  4888.9 2290.54  4929.0 2290.65  4949.0 2287.49
  4979.1 2286.56  4982.4 2283.54  4983.5 2282.94  5036.3 2283.54  5039.8 2293.14
  5050.0 2294.50  5056.2 2297.40  5061.3 2297.31  5080.5 2305.46  5087.3 2306.16
  5109.6 2308.46  5151.6 2310.09  5182.1 2314.20  5211.3 2314.95  5253.3 2315.56
#Mann=7,-1,0
  4297.1    0.07       0  4330.1    0.16       0  4830.5   0.035       0
  4982.4   0.035       0  5036.3   0.035       0  5087.3    0.16       0
  5211.3    0.07       0
Bank Sta=4982.4,5036.3
Exp/Cntr=0.3,0.1

Type RM Length L Ch R = 1,284000,500,500,500
BEGIN DESCRIPTION:
Sweetwater Creek 566.0
END DESCRIPTION:
XS GIS Cut Line= 3
      1371654.98      6810437.99      1372152.92      6810630.64
      1372254.97      6810588.01
#Sta/Elev= 30
  4466.1 2304.92  4481.1 2305.20  4505.7 2302.95  4511.0 2303.81  4560.2 2297.51
  4590.1 2294.96  4650.0 2294.01  4669.2 2296.10  4674.6 2294.77  4685.0 2295.81
  4713.6 2295.08  4744.9 2293.65  4753.7 2291.41  4789.0 2288.55  4852.1 2286.14
  4937.9 2289.88  4947.2 2287.58  4952.6 2287.37  4959.3 2285.18  4986.1 2284.19
  4987.2 2283.59  5040.1 2284.19  5043.0 2291.91  5048.4 2291.20  5066.8 2297.11
  5072.2 2296.01  5078.1 2298.91  5096.0 2304.16  5107.9 2309.66  5110.6 2309.66
#Mann=5,-1,0
  4466.1    0.07       0  4685.0    0.16       0  4713.6    0.07       0
  4986.1    0.07       0  5040.1    0.16       0
Bank Sta=4986.1,5040.1
Exp/Cntr=0.3,0.1

Type RM Length L Ch R = 1,283500,500,500,500
BEGIN DESCRIPTION:
Sweetwater Creek 565.0
END DESCRIPTION:
XS GIS Cut Line= 3
      1371604.99      6810838.00      1371800.95      6810885.74
      1372205.01      6810988.00
#Sta/Elev= 30
  4798.3 2302.94  4911.5 2298.91  4921.8 2297.05  4932.1 2293.24  4946.9 2286.81
  4952.7 2282.42  4963.0 2283.62  4973.1 2283.23  4983.4 2284.09  4987.5 2281.23
  4988.6 2280.63  5041.5 2281.23  5045.4 2283.21  5055.8 2284.33  5065.6 2283.69
  5086.7 2287.42  5106.6 2286.97  5113.5 2287.74  5117.6 2288.60  5128.0 2287.51
  5147.6 2287.87  5152.8 2288.55  5169.2 2293.66  5193.8 2292.74  5200.2 2293.88
  5282.7 2295.08  5316.8 2297.38  5352.7 2301.04  5365.2 2300.77  5416.8 2304.53
#Mann=5,-1,0
  4798.3    0.16       0  4973.1    0.07       0  4987.5    0.07       0
  5041.5    0.07       0  5113.5    0.16       0
Bank Sta=4987.5,5041.5
Exp/Cntr=0.3,0.1

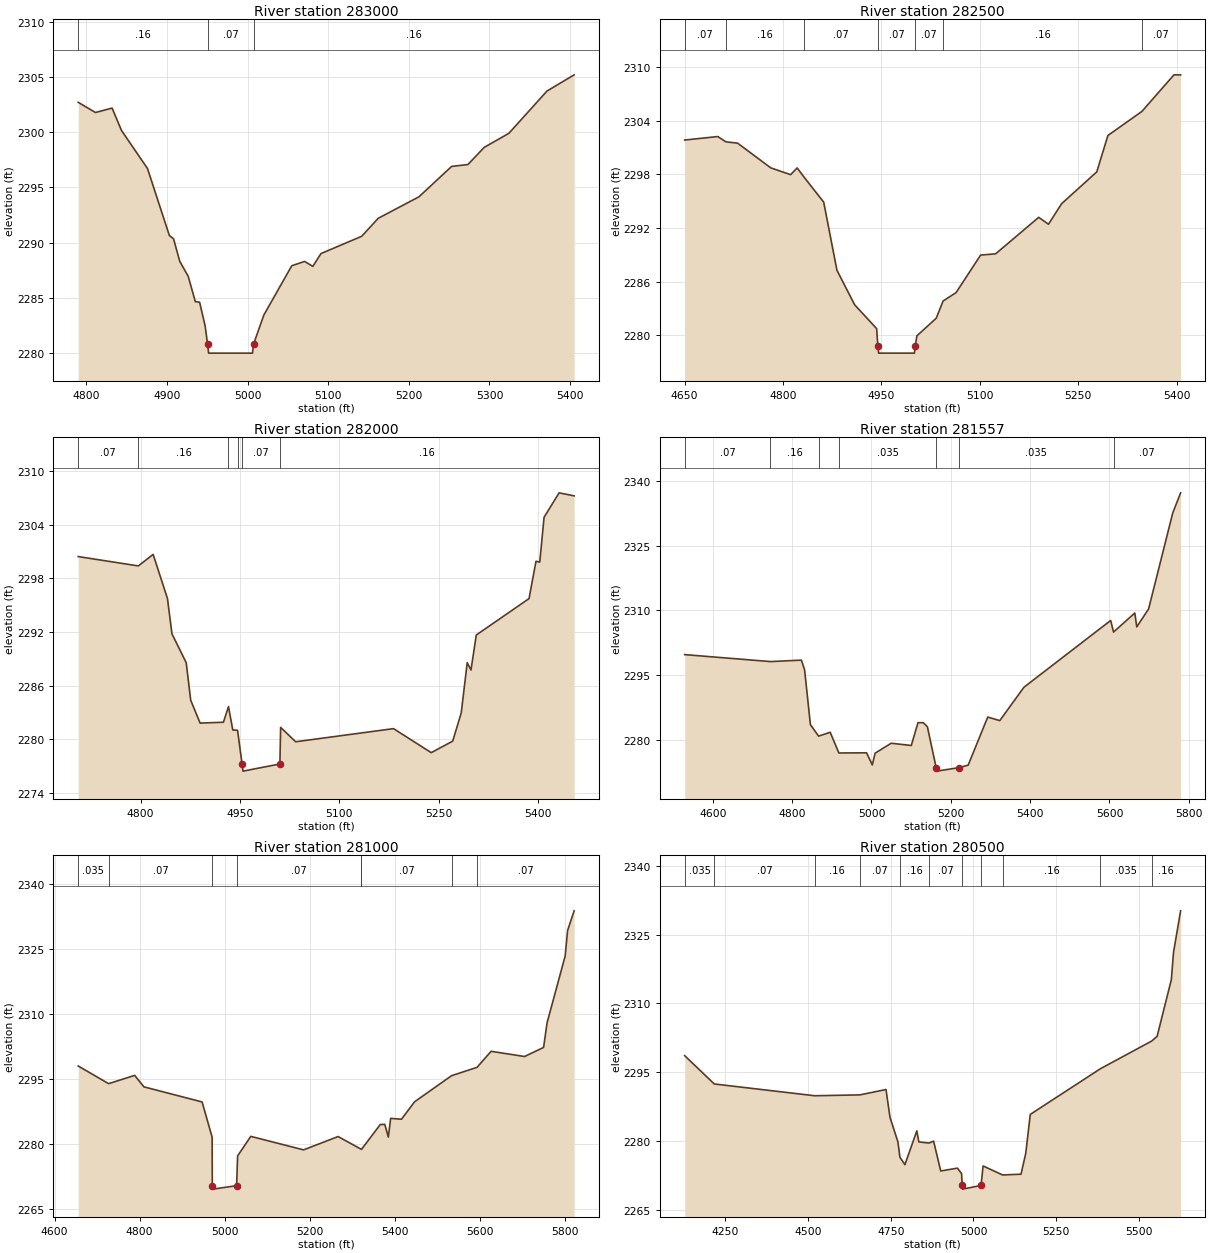
Type RM Length L Ch R = 1,283000,500,500,500
BEGIN DESCRIPTION:
Sweetwater Creek 564.0
END DESCRIPTION:
XS GIS Cut Line= 3
      1371604.98      6811287.99      1371805.05      6811351.48
      1372205.04      6811287.99
#Sta/Elev= 30
  4790.1 2302.70  4811.5 2301.78  4832.1 2302.18  4843.8 2300.15  4876.0 2296.71
  4903.1 2290.65  4908.3 2290.35  4916.0 2288.31  4926.5 2286.95  4935.3 2284.66
  4940.6 2284.61  4947.5 2282.46  4950.5 2280.80  4951.8 2280.00  5006.2 2280.00
  5007.5 2280.80  5020.2 2283.44  5054.9 2287.91  5070.8 2288.30  5081.0 2287.85
  5091.1 2289.01  5141.7 2290.58  5162.0 2292.20  5212.6 2294.15  5253.1 2296.90
  5273.3 2297.07  5293.6 2298.63  5324.0 2299.89  5371.3 2303.72  5405.0 2305.19
#Mann=3,-1,0
  4790.1    0.16       0  4950.5    0.07       0  5007.5    0.16       0
Bank Sta=4950.5,5007.5
Exp/Cntr=0.3,0.1

Type RM Length L Ch R = 1,282500,500,500,500
BEGIN DESCRIPTION:
Sweetwater Creek 563.0
END DESCRIPTION:
XS GIS Cut Line= 3
      1371505.03      6811788.00      1371851.76      6811834.97
      1372255.03      6811788.00
#Sta/Elev= 30
  4650.1 2301.82  4700.5 2302.21  4712.9 2301.62  4730.8 2301.47  4781.3 2298.71
  4811.5 2297.95  4821.6 2298.70  4832.4 2297.64  4862.0 2294.88  4882.2 2287.26
  4909.1 2283.41  4942.7 2280.74  4944.5 2278.80  4945.8 2278.00  5000.2 2278.00
  5001.5 2278.80  5004.1 2279.94  5033.5 2281.90  5044.0 2283.83  5063.7 2284.76
  5101.2 2288.96  5124.1 2289.10  5189.7 2293.18  5204.6 2292.41  5224.7 2294.71
  5278.2 2298.26  5295.2 2302.33  5347.0 2305.02  5395.9 2309.11  5406.0 2309.10
#Mann=7,-1,0
  4650.1    0.07       0  4712.9    0.16       0  4832.4    0.07       0
  4944.5    0.07       0  5001.5    0.07       0  5044.0    0.16       0
  5347.0    0.07       0
Bank Sta=4944.5,5001.5
Exp/Cntr=0.3,0.1

Type RM Length L Ch R = 1,282000,443,443,443
BEGIN DESCRIPTION:
Sweetwater Creek 562.0
END DESCRIPTION:
XS GIS Cut Line= 3
      1371554.97      6812087.97      1371754.98      6812303.59
      1372154.98      6812088.01
#Sta/Elev= 30
  4705.9 2300.45  4796.6 2299.40  4819.0 2300.69  4840.6 2295.75  4847.4 2291.79
  4868.9 2288.56  4875.7 2284.35  4889.9 2281.79  4925.1 2281.89  4932.7 2283.64
  4939.2 2281.02  4946.4 2280.99  4953.2 2277.21  4954.6 2276.41  5010.3 2277.21
  5011.4 2281.31  5034.1 2279.70  5181.8 2281.17  5238.7 2278.48  5271.1 2279.77
  5284.0 2282.94  5293.0 2288.56  5298.7 2287.74  5306.7 2291.66  5386.3 2295.74
  5396.8 2299.92  5402.5 2299.83  5409.0 2304.85  5431.7 2307.59  5454.4 2307.25
#Mann=6,-1,0
  4705.9    0.07       0  4796.6    0.16       0  4932.7    0.12       0
  4946.4    0.16       0  4953.2    0.07       0  5010.3    0.16       0
Bank Sta=4953.2,5010.3
Exp/Cntr=0.3,0.1

Type RM Length L Ch R = 1,281557,557,557,557
BEGIN DESCRIPTION:
Sweetwater Creek 561.0
END DESCRIPTION:
XS GIS Cut Line= 3
      1371330.25      6812419.65      1371705.94      6812703.39
      1372474.56      6812831.96
#Sta/Elev= 30
  4529.2 2299.72  4745.4 2298.10  4823.4 2298.44  4831.5 2296.17  4846.1 2283.48
  4866.8 2280.81  4896.0 2281.70  4917.9 2276.90  4987.7 2276.94  5002.1 2274.13
  5009.2 2276.85  5049.7 2279.16  5100.4 2278.64  5117.3 2283.93  5130.9 2283.92
  5141.0 2282.98  5163.1 2273.49  5164.5 2272.69  5220.2 2273.49  5243.8 2274.08
  5293.1 2285.23  5323.5 2284.41  5384.3 2292.14  5603.0 2307.64  5610.2 2304.95
  5663.8 2309.37  5668.8 2306.16  5698.6 2310.31  5759.5 2332.59  5779.3 2337.25
#Mann=7,-1,0
  4529.2    0.07       0  4745.4    0.16       0  4866.8    0.12       0
  4917.9   0.035       0  5163.1   0.035       0  5220.2   0.035       0
  5610.2    0.07       0
Bank Sta=5163.1,5220.2
Exp/Cntr=0.3,0.1

Type RM Length L Ch R = 1,281000,500,500,500
BEGIN DESCRIPTION:
Sweetwater Creek 560.0
END DESCRIPTION:
XS GIS Cut Line= 3
      1371362.59      6813297.00      1371679.67      6813162.83
      1372455.00      6812888.00
#Sta/Elev= 30
  4655.7 2298.03  4727.2 2293.95  4788.6 2295.86  4810.3 2293.21  4947.2 2289.72
  4970.8 2281.58  4971.2 2270.38  4972.5 2269.58  5028.4 2270.38  5030.8 2277.25
  5061.7 2281.77  5186.0 2278.65  5267.2 2281.73  5322.0 2278.77  5322.2 2278.76
  5366.4 2284.50  5377.0 2284.55  5385.4 2281.60  5390.8 2285.93  5416.3 2285.73
  5447.2 2289.76  5534.2 2295.79  5594.1 2297.72  5627.2 2301.42  5705.9 2300.22
  5750.7 2302.32  5758.9 2308.01  5801.4 2323.42  5807.2 2329.34  5822.6 2333.88
#Mann=8,-1,0
  4655.7   0.035       0  4727.2    0.07       0  4971.2    0.07       0
  5028.4    0.07       0  5322.0    0.16       0  5322.2    0.07       0
  5534.2   0.035       0  5594.1    0.07       0
Bank Sta=4971.2,5028.4
Exp/Cntr=0.3,0.1

Type RM Length L Ch R = 1,280500,500,500,500
BEGIN DESCRIPTION:
Sweetwater Creek 559.0
END DESCRIPTION:
XS GIS Cut Line= 4
      1371337.14      6813360.40      1371726.18      6813638.40
      1372055.51      6813420.22      1372455.00      6812938.00
#Sta/Elev= 30
  4126.8 2298.60  4216.4 2292.42  4520.0 2289.85  4656.6 2290.04  4735.5 2291.21
  4747.5 2285.15  4771.5 2279.79  4777.6 2276.42  4792.6 2274.81  4828.7 2282.19
  4834.7 2279.78  4865.1 2279.52  4879.4 2279.94  4900.9 2273.43  4951.4 2274.05
  4964.1 2272.84  4965.6 2270.27  4966.9 2269.47  5022.8 2270.27  5029.0 2274.53
  5087.9 2272.56  5143.7 2272.73  5158.0 2277.29  5171.7 2285.78  5383.8 2295.75
  5538.8 2301.79  5555.2 2302.83  5598.2 2315.20  5604.7 2321.13  5626.2 2330.21
#Mann=11,-1,0
  4126.8   0.035       0  4216.4    0.07       0  4520.0    0.16       0
  4656.6    0.07       0  4777.6    0.16       0  4865.1    0.07       0
  4965.6    0.07       0  5022.8    0.07       0  5087.9    0.16       0
  5383.8   0.035       0  5538.8    0.16       0
Bank Sta=4965.6,5022.8
Exp/Cntr=0.3,0.1

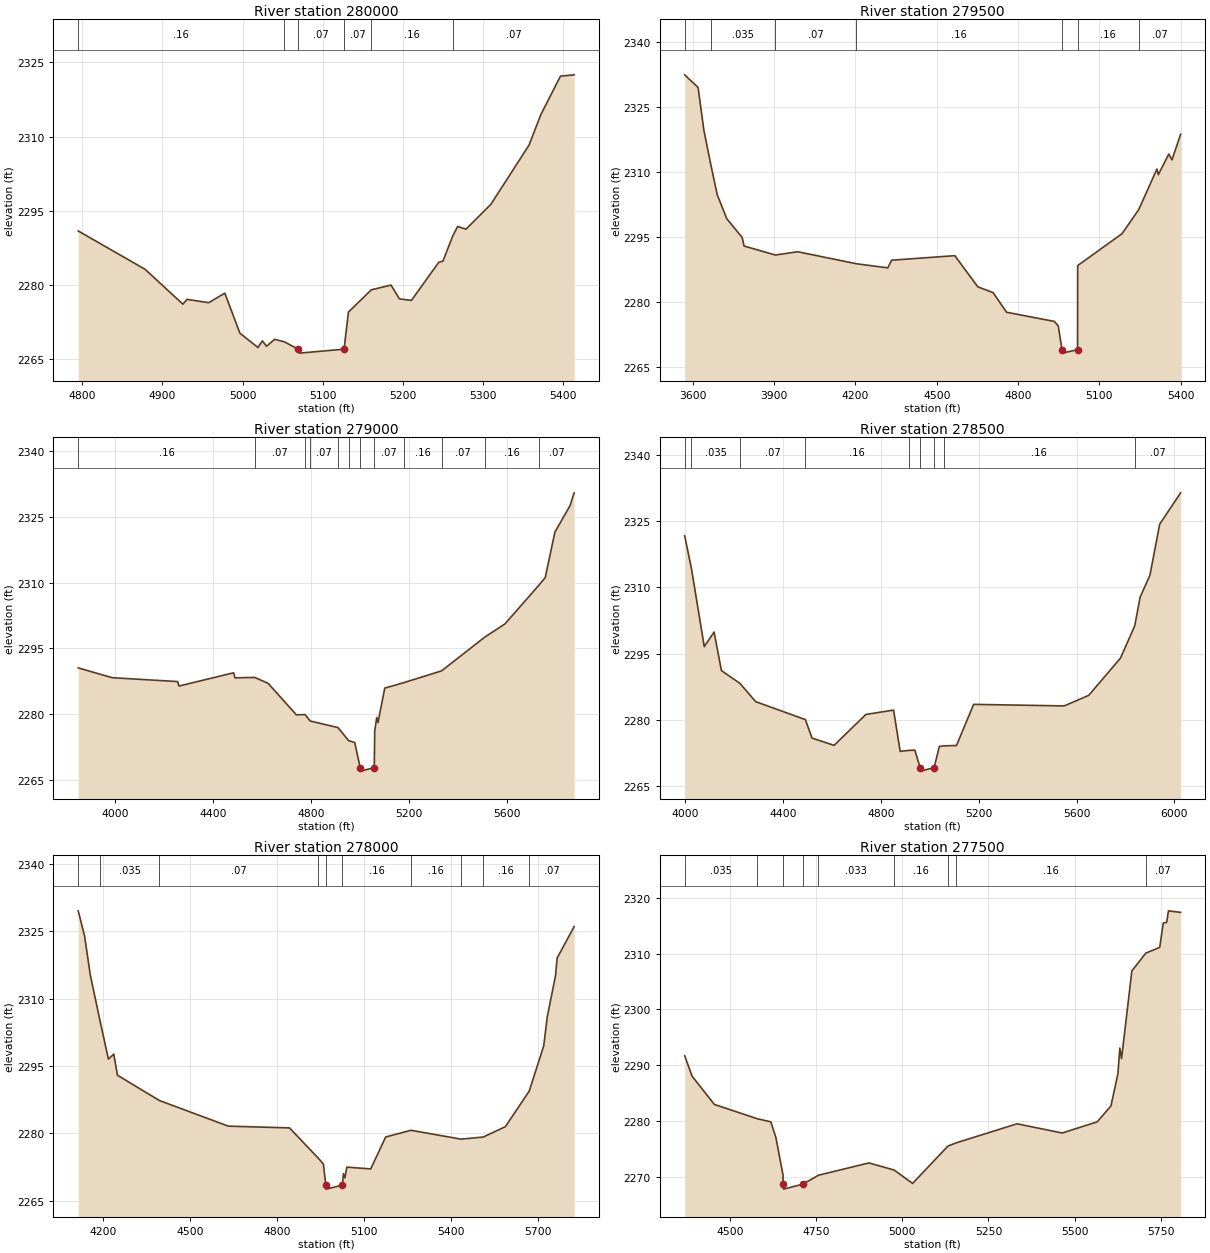
Type RM Length L Ch R = 1,280000,500,500,500
BEGIN DESCRIPTION:
Sweetwater Creek 558.0
END DESCRIPTION:
XS GIS Cut Line= 3
      1371904.99      6813838.00      1372106.50      6813876.21
      1372505.02      6813988.00
#Sta/Elev= 30
  4794.9 2290.96  4878.4 2283.20  4925.6 2276.16  4930.7 2277.13  4957.8 2276.46
  4977.9 2278.39  4996.7 2270.31  5019.2 2267.41  5024.8 2268.74  5030.0 2267.66
  5040.0 2269.06  5052.1 2268.56  5069.5 2267.07  5070.8 2266.27  5126.7 2267.07
  5132.2 2274.57  5160.8 2279.07  5185.4 2280.01  5195.8 2277.23  5210.8 2276.93
  5244.9 2284.62  5250.1 2284.85  5262.3 2289.91  5268.5 2291.86  5278.9 2291.31
  5310.0 2296.35  5357.6 2308.30  5372.3 2314.45  5396.8 2322.23  5413.9 2322.50
#Mann=6,-1,0
  4794.9    0.16       0  5052.1    0.07       0  5069.5    0.07       0
  5126.7    0.07       0  5160.8    0.16       0  5262.3    0.07       0
Bank Sta=5069.5,5126.7
Exp/Cntr=0.3,0.1

Type RM Length L Ch R = 1,279500,500,500,500
BEGIN DESCRIPTION:
Sweetwater Creek 557.0
END DESCRIPTION:
XS GIS Cut Line= 3
      1371154.97      6813337.97      1372155.29      6814360.42
      1372546.02      6814274.35
#Sta/Elev= 30
  3569.6 2332.51  3619.1 2329.59  3640.3 2319.75  3667.2 2311.40  3689.9 2304.75
  3725.2 2299.22  3781.7 2294.91  3788.9 2292.92  3904.1 2290.84  3986.9 2291.59
  4203.6 2288.82  4319.2 2287.87  4333.4 2289.64  4566.7 2290.69  4651.6 2283.48
  4708.1 2282.14  4757.7 2277.60  4934.4 2275.48  4948.6 2274.43  4962.3 2268.95
  4963.7 2268.15  5019.7 2268.95  5020.2 2288.40  5184.0 2295.78  5245.4 2301.33
  5312.7 2310.73  5317.8 2309.42  5356.4 2314.18  5368.3 2312.84  5400.1 2318.76
#Mann=7,-1,0
  3569.6    0.07       0  3667.2   0.035       0  3904.1    0.07       0
  4203.6    0.16       0  4962.3    0.07       0  5019.7    0.16       0
  5245.4    0.07       0
Bank Sta=4962.3,5019.7
Exp/Cntr=0.3,0.1

Type RM Length L Ch R = 1,279000,500,500,500
BEGIN DESCRIPTION:
Sweetwater Creek 556.0
END DESCRIPTION:
XS GIS Cut Line= 3
      1371404.98      6813787.96      1371956.96      6814797.51
      1372811.26      6814617.77
#Sta/Elev= 30
  3849.4 2290.55  3988.4 2288.31  4255.0 2287.43  4260.7 2286.41  4483.6 2289.43
  4489.3 2288.28  4569.6 2288.37  4624.4 2287.02  4739.7 2279.84  4774.9 2279.90
  4796.2 2278.43  4909.6 2276.93  4952.7 2273.95  4977.8 2273.51  5000.0 2267.80
  5001.3 2267.00  5057.4 2267.80  5059.3 2276.14  5067.5 2279.25  5072.6 2278.08
  5100.2 2285.94  5179.0 2287.20  5332.1 2289.87  5508.1 2297.56  5590.7 2300.58
  5730.4 2309.49  5754.9 2311.13  5794.5 2321.53  5856.4 2327.57  5873.0 2330.48
#Mann=12,-1,0
  3849.4    0.16       0  4569.6    0.07       0  4774.9    0.16       0
  4796.2    0.07       0  4909.6    0.16       0  4952.7    0.07       0
  5000.0    0.07       0  5057.4    0.07       0  5179.0    0.16       0
  5332.1    0.07       0  5508.1    0.16       0  5730.4    0.07       0
Bank Sta=5000,5057.4
Exp/Cntr=0.3,0.1

Type RM Length L Ch R = 1,278500,500,500,500
BEGIN DESCRIPTION:
Sweetwater Creek 555.0
END DESCRIPTION:
XS GIS Cut Line= 3
      1370704.99      6815238.00      1371705.46      6815208.60
      1372730.43      6815216.42
#Sta/Elev= 30
  3999.1 2321.65  4026.7 2314.28  4079.1 2296.59  4119.2 2299.88  4149.2 2291.16
  4224.9 2288.26  4289.2 2284.12  4492.3 2280.06  4519.3 2275.89  4609.4 2274.23
  4739.4 2281.23  4852.4 2282.21  4879.5 2272.87  4914.2 2273.09  4939.5 2273.14
  4960.8 2269.20  4962.2 2268.40  5018.2 2269.20  5039.5 2274.00  5058.0 2274.12
  5109.5 2274.20  5179.5 2283.51  5549.6 2283.16  5649.6 2285.55  5779.6 2294.00
  5837.6 2301.29  5859.6 2307.78  5899.6 2312.74  5939.6 2324.30  6025.0 2331.39
#Mann=9,-1,0
  3999.1    0.07       0  4026.7   0.035       0  4224.9    0.07       0
  4492.3    0.16       0  4914.2    0.07       0  4960.8    0.07       0
  5018.2    0.07       0  5058.0    0.16       0  5837.6    0.07       0
Bank Sta=4960.8,5018.2
Exp/Cntr=0.3,0.1

Type RM Length L Ch R = 1,278000,500,500,500
BEGIN DESCRIPTION:
Sweetwater Creek 554.0
END DESCRIPTION:
XS GIS Cut Line= 3
      1370655.00      6815388.00      1371505.27      6815634.91
      1372304.99      6815838.00
#Sta/Elev= 30
  4114.6 2329.52  4136.6 2323.92  4156.3 2315.24  4190.3 2304.92  4218.7 2296.55
  4237.2 2297.64  4250.0 2292.95  4394.7 2287.32  4632.3 2281.62  4843.5 2281.23
  4942.0 2274.53  4960.3 2273.19  4968.4 2268.51  4969.8 2267.61  5026.1 2268.51
  5029.2 2271.05  5034.3 2270.10  5041.0 2272.50  5123.5 2272.11  5175.1 2279.21
  5262.4 2280.70  5435.1 2278.73  5511.7 2279.20  5587.8 2281.50  5670.1 2289.41
  5720.2 2299.49  5732.3 2305.92  5761.1 2315.17  5766.3 2318.99  5825.1 2326.01
#Mann=10,-1,0
  4114.6    0.07       0  4190.3   0.035       0  4394.7    0.07       0
  4942.0    0.16       0  4968.4    0.07       0  5026.1    0.16       0
  5262.4    0.16       0  5435.1    0.07       0  5511.7    0.16       0
  5670.1    0.07       0
Bank Sta=4968.4,5026.1
Exp/Cntr=0.3,0.1

Type RM Length L Ch R = 1,277500,500,500,500
BEGIN DESCRIPTION:
Sweetwater Creek 553.0
END DESCRIPTION:
XS GIS Cut Line= 3
      1370905.02      6816487.99      1371405.60      6816102.68
      1372205.02      6815988.00
#Sta/Elev= 30
  4368.3 2291.70  4390.0 2288.04  4454.4 2282.99  4578.6 2280.43  4618.4 2279.87
  4632.9 2277.10  4653.7 2270.36  4653.9 2268.72  4655.2 2267.82  4711.6 2268.72
  4756.6 2270.31  4902.9 2272.51  4976.1 2271.24  5029.7 2268.84  5132.5 2275.54
  5156.9 2276.12  5332.8 2279.52  5464.1 2277.87  5565.6 2279.87  5605.5 2282.73
  5625.7 2288.54  5631.2 2293.09  5636.2 2291.20  5666.1 2306.90  5706.6 2310.09
  5747.0 2311.11  5757.1 2315.46  5767.2 2315.60  5772.3 2317.66  5807.6 2317.38
#Mann=9,-1,0
  4368.3   0.035       0  4578.6    0.16       0  4653.9    0.07       0
  4711.6    0.16       0  4756.6   0.033       0  4976.1    0.16       0
  5132.5    0.07       0  5156.9    0.16       0  5706.6    0.07       0
Bank Sta=4653.9,4711.6
Exp/Cntr=0.3,0.1