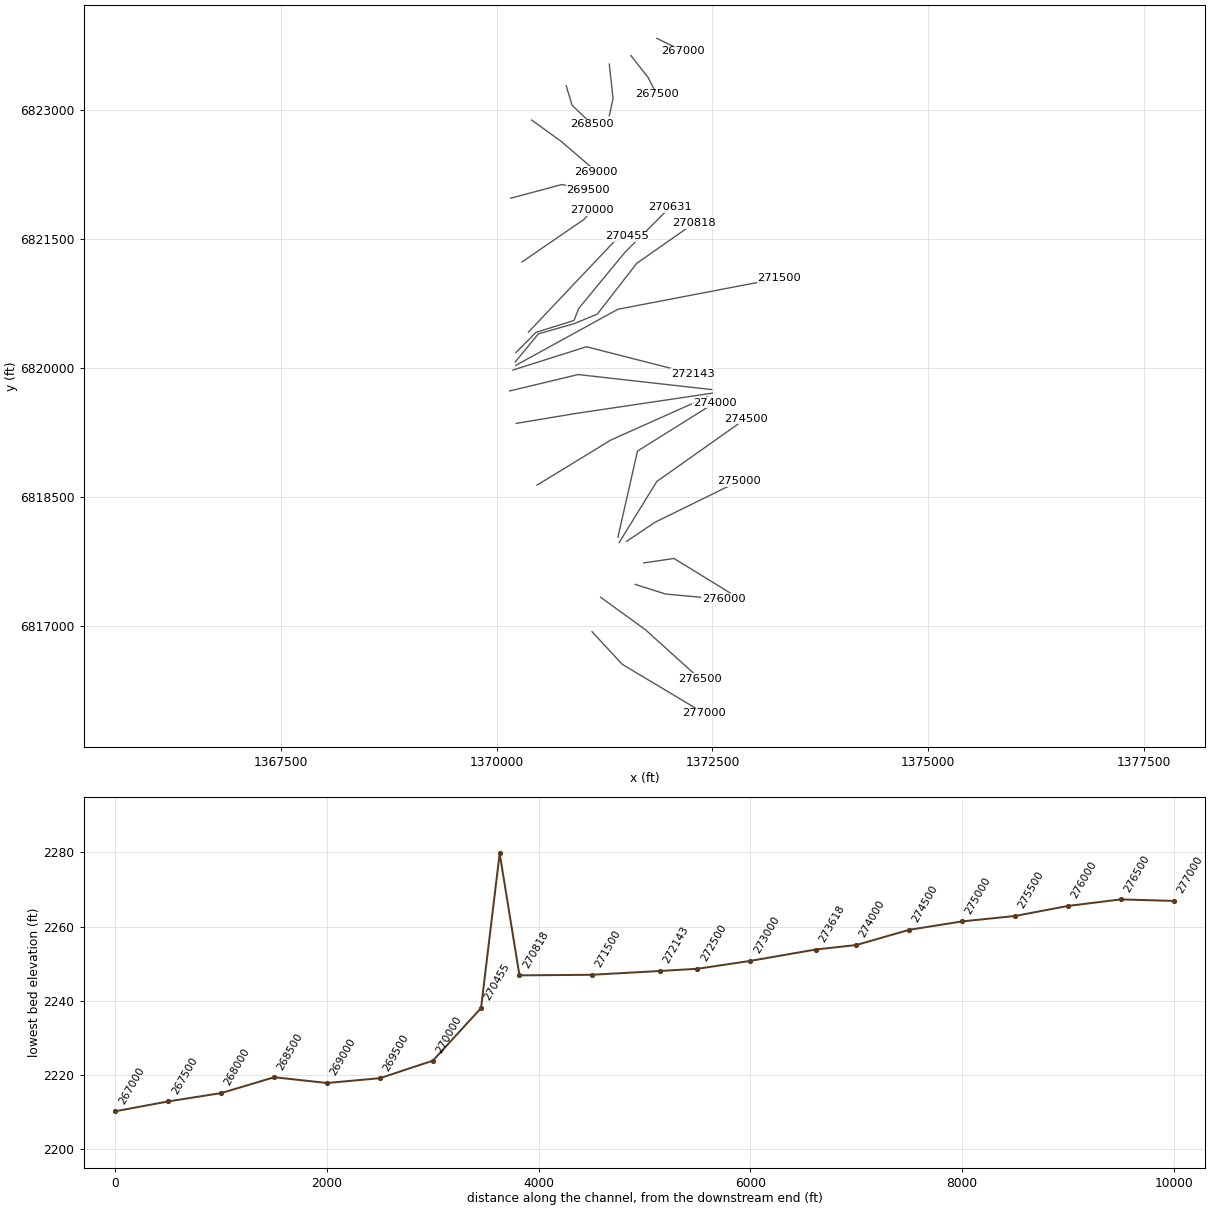
HEC-RAS study Sweetwater Creek.prj: Sweetwater Creek Base Level Engineering

--- Sweetwater Creek.g01 (geometry) --- (continued)

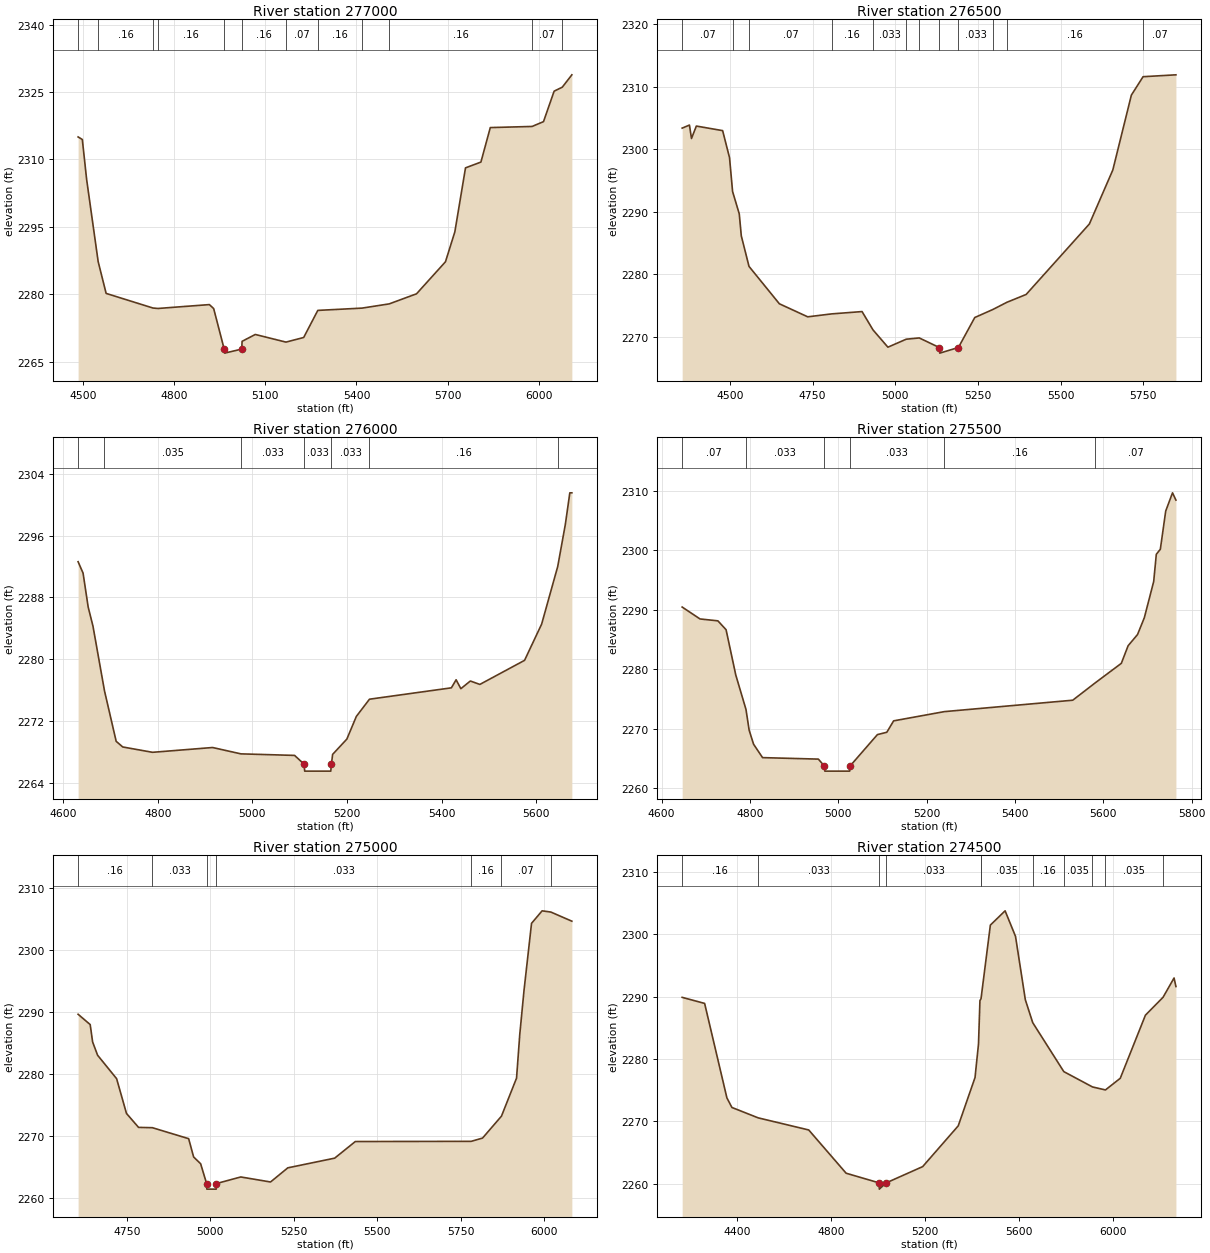
Type RM Length L Ch R = 1,277000,500,500,500
BEGIN DESCRIPTION:
Sweetwater Creek 552.0
END DESCRIPTION:
XS GIS Cut Line= 3
      1371104.98      6816938.03      1371454.56      6816558.90
      1372404.98      6815988.01
#Sta/Elev= 30
  4484.3 2315.00  4498.2 2314.43  4512.4 2305.53  4550.3 2287.28  4576.5 2280.21
  4730.5 2276.96  4747.2 2276.86  4916.2 2277.72  4930.3 2276.84  4964.9 2267.83
  4966.3 2266.93  5022.7 2267.83  5023.8 2269.55  5067.2 2271.08  5168.2 2269.38
  5226.5 2270.41  5272.9 2276.43  5418.6 2276.94  5507.9 2277.88  5597.7 2280.12
  5692.9 2287.24  5723.8 2293.91  5758.8 2308.12  5809.5 2309.41  5840.4 2317.08
  5977.9 2317.33  6015.4 2318.40  6050.4 2325.18  6077.2 2326.06  6108.7 2328.81
#Mann=12,-1,0
  4484.3    0.07       0  4550.3    0.16       0  4730.5   0.035       0
  4747.2    0.16       0  4964.9   0.033       0  5022.7    0.16       0
  5168.2    0.07       0  5272.9    0.16       0  5418.6    0.07       0
  5507.9    0.16       0  5977.9    0.07       0  6077.2    0.16       0
Bank Sta=4964.9,5022.7
Exp/Cntr=0.3,0.1

Type RM Length L Ch R = 1,276500,500,500,500
BEGIN DESCRIPTION:
Sweetwater Creek 551.0
END DESCRIPTION:
XS GIS Cut Line= 3
      1371205.02      6817337.98      1371726.21      6816958.68
      1372354.96      6816388.03
#Sta/Elev= 30
  4355.4 2303.35  4377.4 2303.84  4383.6 2301.69  4398.3 2303.68  4477.8 2302.95
  4498.7 2298.62  4507.9 2293.21  4528.1 2289.63  4534.3 2286.11  4557.6 2281.22
  4649.4 2275.24  4735.2 2273.15  4807.7 2273.62  4899.6 2273.99  4932.7 2271.06
  4977.8 2268.29  5033.2 2269.57  5072.6 2269.77  5133.3 2268.24  5134.7 2267.34
  5191.1 2268.24  5240.6 2273.04  5295.2 2274.32  5337.9 2275.48  5396.0 2276.73
  5587.3 2288.01  5658.2 2296.65  5714.3 2308.63  5749.7 2311.58  5849.1 2311.88
#Mann=12,-1,0
  4355.4    0.07       0  4507.9    0.16       0  4557.6    0.07       0
  4807.7    0.16       0  4932.7   0.033       0  5033.2   0.035       0
  5072.6   0.033       0  5133.3   0.033       0  5191.1   0.033       0
  5295.2    0.07       0  5337.9    0.16       0  5749.7    0.07       0
Bank Sta=5133.3,5191.1
Exp/Cntr=0.3,0.1

Type RM Length L Ch R = 1,276000,500,500,500
BEGIN DESCRIPTION:
Sweetwater Creek 550.0
END DESCRIPTION:
XS GIS Cut Line= 3
      1371605.03      6817487.99      1371956.15      6817376.13
      1372628.65      6817313.66
#Sta/Elev= 30
  4631.5 2292.62  4642.0 2291.15  4652.8 2286.76  4662.9 2284.31  4687.3 2275.94
  4712.0 2269.42  4725.9 2268.69  4788.9 2268.00  4915.8 2268.62  4975.7 2267.80
  5089.2 2267.60  5109.3 2266.47  5110.6 2265.57  5165.7 2265.57  5167.1 2266.47
  5169.6 2267.73  5199.7 2269.71  5219.8 2272.64  5247.5 2274.86  5420.7 2276.33
  5430.7 2277.37  5440.7 2276.22  5460.8 2277.21  5480.9 2276.77  5575.4 2279.88
  5611.5 2284.56  5645.5 2292.00  5661.7 2297.47  5671.1 2301.52  5675.4 2301.52
#Mann=7,-1,0
  4631.5    0.16       0  4687.3   0.035       0  4975.7   0.033       0
  5109.3   0.033       0  5167.1   0.033       0  5247.5    0.16       0
  5645.5    0.07       0
Bank Sta=5109.3,5167.1
Exp/Cntr=0.3,0.1

Type RM Length L Ch R = 1,275500,500,500,500
BEGIN DESCRIPTION:
Sweetwater Creek 549.0
END DESCRIPTION:
XS GIS Cut Line= 3
      1371704.99      6817738.00      1372054.60      6817789.58
      1372705.02      6817387.99
#Sta/Elev= 30
  4646.6 2290.44  4687.0 2288.44  4727.5 2288.12  4746.0 2286.63  4767.9 2279.04
  4791.1 2273.22  4798.2 2269.75  4808.3 2267.38  4828.6 2265.13  4954.9 2264.88
  4968.1 2263.76  4969.6 2262.86  5025.8 2262.86  5027.2 2263.76  5088.6 2269.00
  5109.9 2269.39  5125.3 2271.31  5240.0 2272.86  5530.8 2274.78  5580.7 2277.64
  5640.8 2280.98  5656.2 2283.94  5677.5 2285.82  5692.9 2288.65  5714.1 2294.74
  5720.0 2299.31  5729.1 2300.15  5741.3 2306.58  5756.7 2309.64  5764.4 2308.42
#Mann=6,-1,0
  4646.6    0.07       0  4791.1   0.033       0  4968.1   0.033       0
  5027.2   0.033       0  5240.0    0.16       0  5580.7    0.07       0
Bank Sta=4968.1,5027.2
Exp/Cntr=0.3,0.1

Type RM Length L Ch R = 1,275000,500,500,500
BEGIN DESCRIPTION:
Sweetwater Creek 548.0
END DESCRIPTION:
XS GIS Cut Line= 3
      1371504.99      6817987.99      1371832.99      6818209.70
      1372804.98      6818687.99
#Sta/Elev= 30
  4604.1 2289.58  4640.3 2287.92  4647.6 2285.12  4662.5 2282.98  4719.5 2279.20
  4749.0 2273.60  4785.2 2271.35  4826.6 2271.30  4935.3 2269.53  4950.2 2266.58
  4971.2 2265.49  4989.1 2262.30  4989.8 2261.40  5017.9 2261.40  5018.6 2262.30
  5091.4 2263.36  5180.6 2262.55  5232.3 2264.83  5372.7 2266.39  5434.6 2269.07
  5781.9 2269.10  5815.8 2269.63  5872.4 2273.16  5917.6 2279.29  5927.3 2286.35
  5940.0 2293.44  5962.5 2304.23  5994.2 2306.25  6020.5 2306.05  6083.3 2304.58
#Mann=7,-1,0
  4604.1    0.16       0  4826.6   0.033       0  4989.1   0.033       0
  5018.6   0.033       0  5781.9    0.16       0  5872.4    0.07       0
  6020.5   0.035       0
Bank Sta=4989.1,5018.6
Exp/Cntr=0.3,0.1

Type RM Length L Ch R = 1,274500,500,500,500
BEGIN DESCRIPTION:
Sweetwater Creek 547.0
END DESCRIPTION:
XS GIS Cut Line= 3
      1371418.77      6817973.75      1371855.03      6818684.31
      1372887.39      6819416.93
#Sta/Elev= 30
  4166.2 2289.89  4261.7 2288.92  4356.4 2273.77  4377.7 2272.23  4489.6 2270.56
  4704.4 2268.62  4863.5 2261.68  5004.0 2260.13  5004.7 2259.13  5033.6 2260.13
  5188.9 2262.74  5340.2 2269.28  5411.6 2277.03  5426.4 2282.43  5432.5 2289.37
  5435.9 2289.59  5437.1 2289.67  5476.8 2301.48  5539.5 2303.77  5583.8 2299.67
  5625.6 2289.50  5657.0 2285.83  5789.1 2277.98  5911.1 2275.52  5966.2 2275.04
  6029.2 2276.91  6136.2 2287.03  6211.1 2289.90  6258.0 2293.00  6265.9 2291.63
#Mann=11,-1,0
  4166.2    0.16       0  4489.6   0.033       0  5004.0   0.033       0
  5033.6   0.033       0  5435.9    0.07       0  5437.1   0.035       0
  5657.0    0.16       0  5789.1   0.035       0  5911.1    0.07       0
  5966.2   0.035       0  6211.1    0.16       0
Bank Sta=5004,5033.6
Exp/Cntr=0.3,0.1

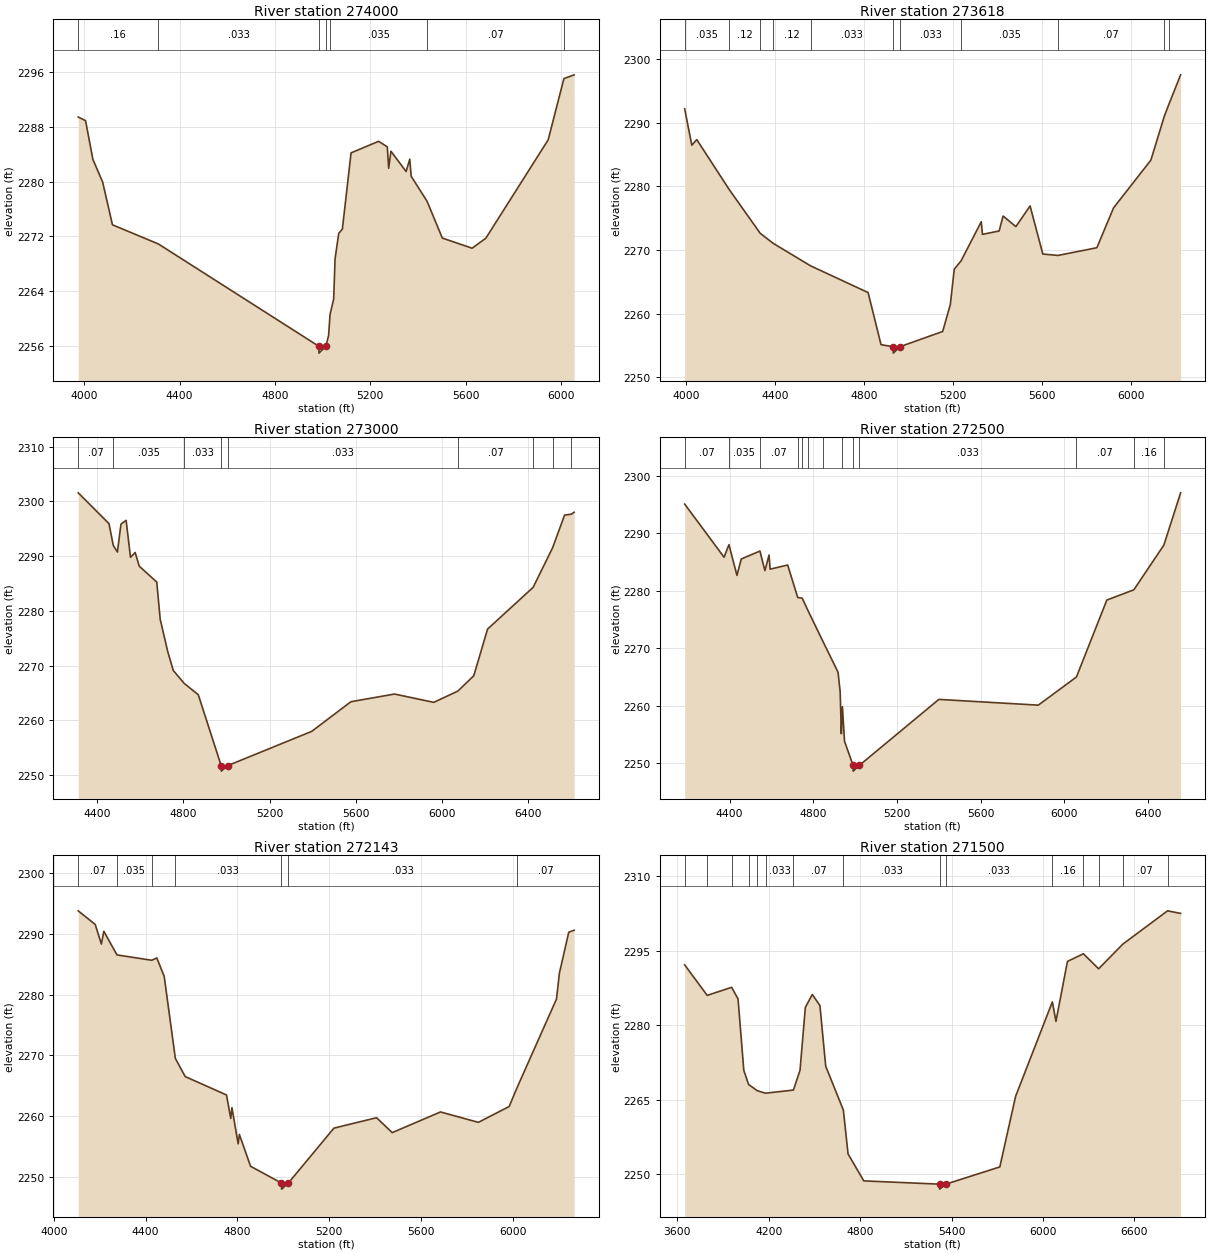
Type RM Length L Ch R = 1,274000,382,382,382
BEGIN DESCRIPTION:
Sweetwater Creek 546.0
END DESCRIPTION:
XS GIS Cut Line= 3
      1371405.00      6818037.98      1371631.55      6819037.93
      1372524.97      6819599.22
#Sta/Elev= 30
  3974.7 2289.39  4005.5 2288.86  4036.2 2283.23  4077.3 2279.91  4118.3 2273.70
  4311.1 2270.91  4984.0 2256.02  4984.7 2255.02  5013.6 2256.02  5025.1 2257.60
  5031.0 2260.63  5046.3 2262.89  5052.2 2268.75  5067.5 2272.44  5082.8 2273.08
  5119.3 2284.17  5234.7 2285.85  5271.2 2285.05  5277.1 2281.93  5286.5 2284.41
  5350.2 2281.46  5365.5 2283.26  5371.4 2280.77  5438.0 2277.13  5502.1 2271.77
  5627.0 2270.29  5684.7 2271.75  5946.2 2286.07  6012.1 2294.98  6055.1 2295.53
#Mann=7,-1,0
  3974.7    0.16       0  4311.1   0.033       0  4984.0   0.033       0
  5013.6   0.033       0  5031.0   0.035       0  5438.0    0.07       0
  6012.1    0.16       0
Bank Sta=4984,5013.6
Exp/Cntr=0.3,0.1

Type RM Length L Ch R = 1,273618,618,618,618
BEGIN DESCRIPTION:
Sweetwater Creek 545.0
END DESCRIPTION:
XS GIS Cut Line= 3
      1370467.64      6818642.16      1371325.03      6819167.81
      1372440.16      6819668.58
#Sta/Elev= 30
  3994.3 2292.17  4026.4 2286.47  4048.6 2287.35  4194.8 2279.49  4333.4 2272.65
  4391.1 2271.08  4559.8 2267.53  4818.4 2263.33  4876.4 2255.15  4931.0 2254.82
  4931.7 2253.82  4960.9 2254.82  5153.4 2257.22  5187.7 2261.44  5205.4 2267.00
  5236.1 2268.31  5326.7 2274.45  5332.2 2272.47  5407.1 2273.00  5424.8 2275.35
  5482.3 2273.69  5546.1 2276.93  5603.4 2269.38  5671.6 2269.16  5846.1 2270.37
  5921.1 2276.63  6088.7 2284.12  6149.3 2291.03  6168.8 2292.81  6222.4 2297.52
#Mann=11,-1,0
  3994.3   0.035       0  4194.8    0.12       0  4333.4   0.035       0
  4391.1    0.12       0  4559.8   0.033       0  4931.0   0.033       0
  4960.9   0.033       0  5236.1   0.035       0  5671.6    0.07       0
  6149.3    0.16       0  6168.8   0.035       0
Bank Sta=4931,4960.9
Exp/Cntr=0.3,0.1

Type RM Length L Ch R = 1,273000,500,500,500
BEGIN DESCRIPTION:
Sweetwater Creek 544.0
END DESCRIPTION:
XS GIS Cut Line= 3
      1370225.72      6819359.95      1370903.84      6819473.71
      1372498.93      6819712.05
#Sta/Elev= 30
  4312.4 2301.58  4455.2 2295.95  4475.0 2291.98  4494.2 2290.77  4510.8 2295.87
  4534.7 2296.55  4555.0 2289.80  4576.5 2290.68  4595.6 2288.18  4676.7 2285.29
  4692.7 2278.50  4727.4 2272.62  4753.3 2269.14  4804.1 2266.77  4869.4 2264.70
  4975.5 2251.75  4976.2 2250.75  5005.4 2251.75  5395.5 2258.01  5577.5 2263.43
  5779.7 2264.83  5961.7 2263.31  6073.4 2265.37  6147.2 2268.17  6211.3 2276.70
  6422.4 2284.31  6512.9 2291.54  6568.4 2297.51  6598.4 2297.67  6612.8 2298.03
#Mann=9,-1,0
  4312.4    0.07       0  4475.0   0.035       0  4804.1   0.033       0
  4975.5   0.033       0  5005.4   0.033       0  6073.4    0.07       0
  6422.4    0.16       0  6512.9   0.035       0  6598.4    0.07       0
Bank Sta=4975.5,5005.4
Exp/Cntr=0.3,0.1

Type RM Length L Ch R = 1,272500,357,357,357
BEGIN DESCRIPTION:
Sweetwater Creek 543.0
END DESCRIPTION:
XS GIS Cut Line= 3
      1370151.94      6819737.56      1370944.01      6819928.25
      1372491.16      6819753.42
#Sta/Elev= 30
  4185.3 2295.08  4373.6 2285.84  4396.9 2288.02  4435.3 2282.68  4455.9 2285.53
  4545.1 2286.91  4569.0 2283.51  4588.8 2286.21  4593.9 2283.76  4677.8 2284.48
  4726.0 2278.83  4747.4 2278.71  4776.0 2276.48  4848.5 2271.04  4918.7 2265.83
  4929.0 2262.40  4934.5 2255.13  4936.3 2256.79  4939.6 2259.83  4949.6 2253.84
  4990.6 2249.62  4991.3 2248.62  5020.5 2249.62  5400.8 2261.10  5876.5 2260.10
  6058.8 2265.00  6204.1 2278.38  6333.4 2280.17  6476.8 2287.94  6557.0 2297.04
#Mann=13,-1,0
  4185.3    0.07       0  4396.9   0.035       0  4545.1    0.07       0
  4726.0   0.035       0  4747.4    0.07       0  4776.0   0.035       0
  4848.5    0.07       0  4936.3   0.033       0  4990.6   0.033       0
  5020.5   0.033       0  6058.8    0.07       0  6333.4    0.16       0
  6476.8   0.035       0
Bank Sta=4990.6,5020.5
Exp/Cntr=0.3,0.1

Type RM Length L Ch R = 1,272143,643,643,643
BEGIN DESCRIPTION:
Sweetwater Creek 542.0
END DESCRIPTION:
XS GIS Cut Line= 3
      1370188.83      6819980.61      1371040.63      6820251.38
      1372269.58      6819936.32
#Sta/Elev= 30
  4106.2 2293.78  4180.5 2291.53  4207.1 2288.32  4218.0 2290.41  4275.3 2286.53
  4426.9 2285.65  4448.9 2286.04  4481.2 2283.00  4529.8 2269.51  4572.7 2266.53
  4752.8 2263.50  4771.4 2259.64  4776.6 2261.41  4803.6 2255.47  4808.9 2257.02
  4857.7 2251.78  4992.5 2249.02  4993.2 2248.02  5022.4 2249.02  5221.3 2258.05
  5407.1 2259.76  5475.5 2257.31  5685.9 2260.71  5851.0 2259.00  5985.2 2261.60
  6020.0 2264.72  6191.7 2279.28  6204.4 2283.53  6245.2 2290.27  6268.7 2290.59
#Mann=7,-1,0
  4106.2    0.07       0  4275.3   0.035       0  4426.9    0.07       0
  4529.8   0.033       0  4992.5   0.033       0  5022.4   0.033       0
  6020.0    0.07       0
Bank Sta=4992.5,5022.4
Exp/Cntr=0.3,0.1

Type RM Length L Ch R = 1,271500,682,682,682
BEGIN DESCRIPTION:
Sweetwater Creek 541.0
END DESCRIPTION:
XS GIS Cut Line= 3
      1370221.31      6820034.84      1371404.87      6820687.53
      1373274.51      6821047.58
#Sta/Elev= 30
  3648.4 2292.12  3796.3 2285.98  3956.8 2287.60  3998.8 2285.25  4036.6 2270.89
  4068.1 2268.05  4125.3 2266.79  4179.3 2266.30  4362.2 2266.93  4405.7 2270.93
  4440.6 2283.58  4486.3 2286.16  4536.3 2283.93  4574.2 2271.73  4690.1 2262.91
  4720.9 2254.09  4824.1 2248.66  5321.3 2248.00  5322.4 2247.00  5363.2 2248.00
  5717.2 2251.47  5821.0 2265.69  6062.1 2284.67  6085.6 2280.75  6161.1 2292.81
  6265.7 2294.35  6365.9 2291.33  6524.6 2296.29  6818.3 2302.99  6904.0 2302.47
#Mann=15,-1,0
  3648.4    0.07       0  3796.3   0.035       0  3956.8    0.07       0
  4068.1   0.033       0  4125.3   0.035       0  4179.3   0.033       0
  4362.2    0.07       0  4690.1   0.033       0  5321.3   0.033       0
  5363.2   0.033       0  6062.1    0.16       0  6265.7    0.07       0
  6365.9   0.035       0  6524.6    0.07       0  6818.3    0.16       0
Bank Sta=5321.3,5363.2
Exp/Cntr=0.3,0.1

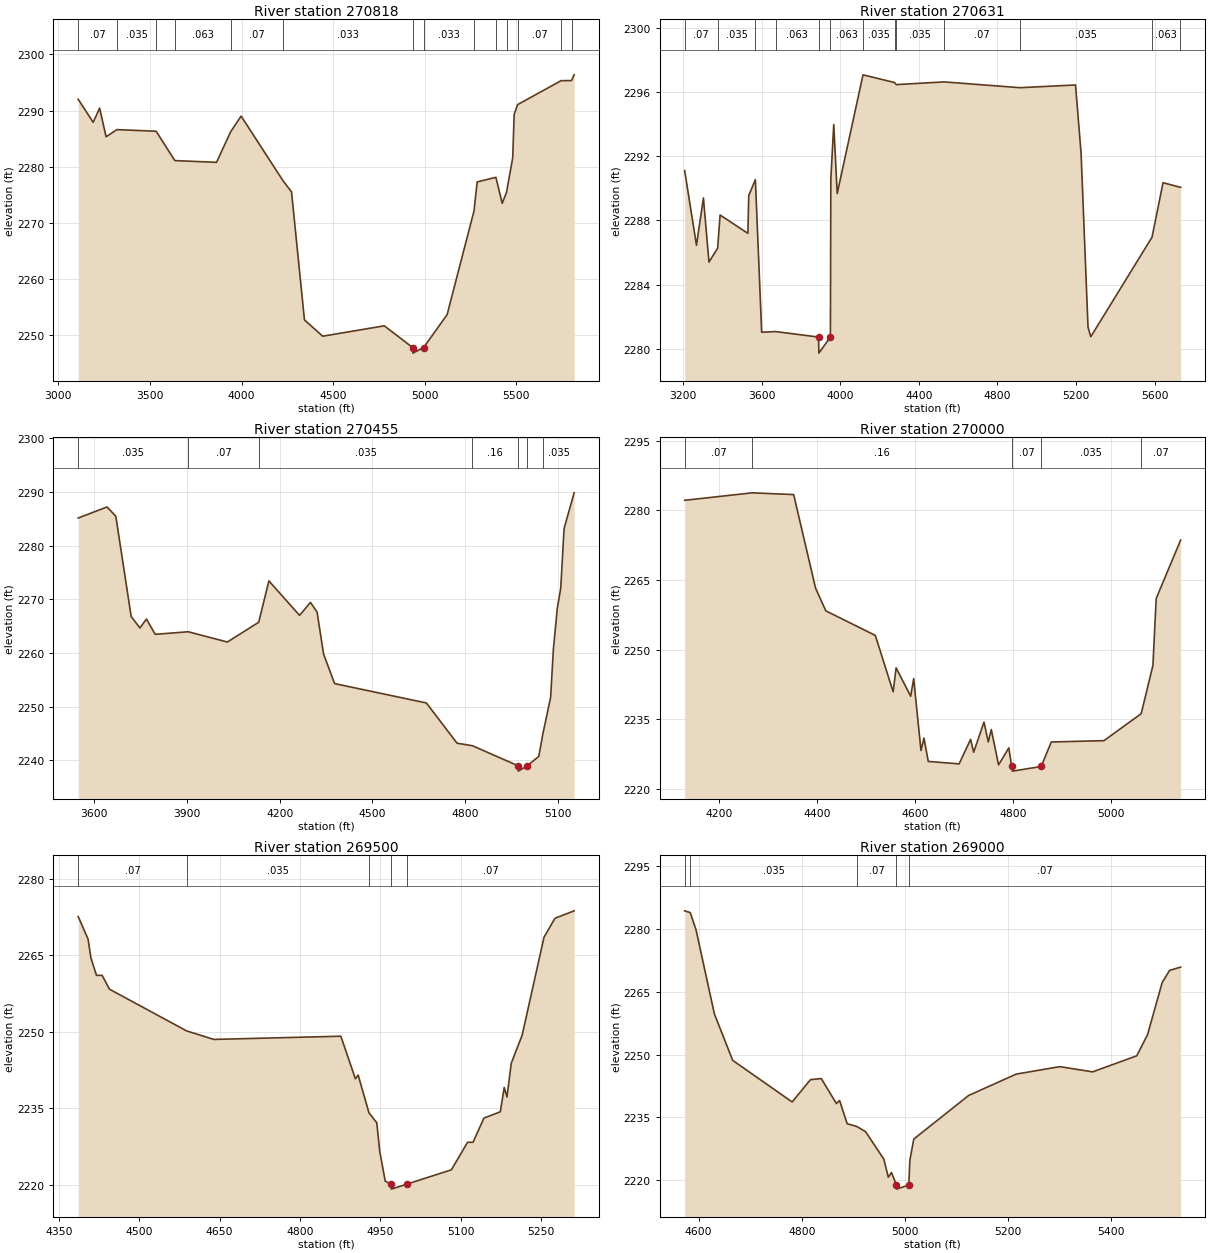
Type RM Length L Ch R = 1,270818,187,187,187
BEGIN DESCRIPTION:
Sweetwater Creek 540.0
END DESCRIPTION:
XS GIS Cut Line= 6
      1370214.85      6820073.94      1370481.84      6820400.56
      1370898.51      6820520.35      1371165.87      6820630.76
      1371622.52      6821221.33      1372289.32      6821689.96
#Sta/Elev= 30
  3108.8 2292.01  3190.5 2287.91  3225.7 2290.43  3260.9 2285.34  3320.1 2286.61
  3534.1 2286.32  3636.2 2281.10  3863.5 2280.79  3940.8 2286.23  3997.8 2289.02
  4226.9 2277.49  4272.8 2275.53  4343.4 2252.75  4443.0 2249.85  4779.0 2251.70
  4933.6 2247.84  4935.1 2246.84  4993.8 2247.84  5121.9 2253.69  5268.7 2272.16
  5285.7 2277.30  5387.9 2278.12  5422.5 2273.50  5446.0 2275.48  5479.7 2281.58
  5487.8 2289.34  5506.5 2291.06  5743.7 2295.32  5800.6 2295.34  5815.0 2296.36
#Mann=14,-1,0
  3108.8    0.07       0  3320.1   0.035       0  3534.1    0.07       0
  3636.2   0.063       0  3940.8    0.07       0  4226.9   0.033       0
  4933.6   0.033       0  4993.8   0.033       0  5268.7   0.035       0
  5387.9    0.07       0  5446.0    0.16       0  5506.5    0.07       0
  5743.7   0.063       0  5800.6   0.035       0
Bank Sta=4933.6,4993.8
Exp/Cntr=0.3,0.1

Type RM Length L Ch R = 1,270631,176,176,176
BEGIN DESCRIPTION:
Sweetwater Creek 4291
END DESCRIPTION:
XS GIS Cut Line= 6
      1370223.49      6820184.57      1370456.24      6820418.96
      1370896.34      6820556.98      1370951.03      6820697.60
      1371489.63      6821353.39      1372007.22      6821872.28
#Sta/Elev= 30
  3208.9 2291.10  3269.0 2286.46  3304.3 2289.40  3332.6 2285.41  3376.6 2286.28
  3389.2 2288.34  3530.6 2287.20  3535.0 2289.55  3568.7 2290.54  3600.8 2281.05
  3671.5 2281.09  3890.3 2280.75  3891.8 2279.75  3950.5 2280.75  3952.8 2290.60
  3967.6 2293.97  3985.2 2289.68  4116.5 2297.06  4277.0 2296.58  4285.9 2296.45
  4528.2 2296.62  4915.9 2296.26  5198.0 2296.43  5226.3 2292.19  5261.6 2281.37
  5275.7 2280.77  5587.4 2286.96  5643.4 2290.35  5729.7 2290.07  5732.9 2290.07
#Mann=13,-1,0
  3208.9    0.07       0  3376.6   0.035       0  3568.7    0.07       0
  3671.5   0.063       0  3890.3   0.035       0  3950.5   0.063       0
  4116.5   0.035       0  4277.0    0.07       0  4285.9   0.035       0
  4528.2    0.07       0  4915.9   0.035       0  5587.4   0.063       0
  5729.7   0.035       0
Bank Sta=3890.3,3950.5
Exp/Cntr=0.3,0.1

Type RM Length L Ch R = 1,270455,455,455,455
BEGIN DESCRIPTION:
Sweetwater Creek 539.0
END DESCRIPTION:
XS GIS Cut Line= 3
      1370368.59      6820422.46      1371365.06      6821478.14
      1371505.00      6821538.00
#Sta/Elev= 30
  3548.3 2285.14  3641.5 2287.20  3669.9 2285.47  3719.6 2266.80  3747.9 2264.67
  3769.0 2266.33  3797.3 2263.48  3903.9 2263.96  4030.7 2262.05  4132.0 2265.73
  4165.0 2273.43  4264.2 2267.01  4299.4 2269.43  4320.8 2267.62  4341.8 2259.82
  4377.4 2254.31  4674.4 2250.70  4773.5 2243.21  4823.2 2242.74  4970.8 2239.01
  4971.6 2238.01  5000.9 2239.01  5037.9 2240.76  5051.0 2244.93  5076.1 2251.75
  5085.1 2260.75  5097.8 2268.38  5108.7 2271.99  5119.6 2283.19  5152.2 2289.83
#Mann=7,-1,0
  3548.3   0.035       0  3903.9    0.07       0  4132.0   0.035       0
  4823.2    0.16       0  4970.8    0.07       0  5000.9    0.16       0
  5051.0   0.035       0
Bank Sta=4970.8,5000.9
Exp/Cntr=0.3,0.1

Type RM Length L Ch R = 1,270000,500,500,500
BEGIN DESCRIPTION:
Sweetwater Creek 538.0
END DESCRIPTION:
XS GIS Cut Line= 3
      1370294.76      6821238.39      1371010.97      6821731.77
      1371105.02      6821838.02
#Sta/Elev= 30
  4130.3 2282.19  4268.2 2283.80  4352.6 2283.42  4397.3 2263.25  4418.2 2258.37
  4519.2 2253.07  4555.5 2240.93  4561.6 2246.08  4591.3 2239.97  4597.4 2243.77
  4612.3 2228.28  4618.4 2230.95  4627.2 2225.92  4690.1 2225.39  4713.5 2230.67
  4719.8 2227.90  4740.8 2234.41  4749.6 2230.12  4755.7 2232.79  4770.6 2225.17
  4791.5 2228.85  4797.3 2224.83  4798.8 2223.83  4857.5 2224.83  4878.1 2230.11
  4985.6 2230.40  5061.5 2236.21  5085.4 2246.60  5092.1 2261.03  5141.9 2273.60
#Mann=5,-1,0
  4130.3    0.07       0  4268.2    0.16       0  4797.3    0.07       0
  4857.5   0.035       0  5061.5    0.07       0
Bank Sta=4797.3,4857.5
Exp/Cntr=0.3,0.1

Type RM Length L Ch R = 1,269500,500,500,500
BEGIN DESCRIPTION:
Sweetwater Creek 537.0
END DESCRIPTION:
XS GIS Cut Line= 3
      1370162.07      6821978.28      1370754.57      6822137.81
      1371060.19      6822078.62
#Sta/Elev= 30
  4386.4 2272.58  4404.8 2268.14  4410.1 2264.46  4420.5 2261.04  4430.9 2261.05
  4444.7 2258.33  4588.4 2250.15  4639.2 2248.47  4876.2 2249.10  4903.3 2240.76
  4908.5 2241.48  4928.6 2234.09  4943.3 2232.10  4948.7 2226.53  4959.0 2220.66
  4969.7 2220.10  4970.4 2219.10  4999.8 2220.10  5082.4 2222.89  5112.5 2228.29
  5122.7 2228.29  5143.0 2233.03  5173.6 2234.28  5180.9 2239.05  5186.0 2237.17
  5194.0 2243.80  5214.3 2249.29  5255.1 2268.52  5275.5 2272.24  5311.3 2273.70
#Mann=5,-1,0
  4386.4    0.07       0  4588.4   0.035       0  4928.6    0.07       0
  4969.7    0.07       0  4999.8    0.07       0
Bank Sta=4969.7,4999.8
Exp/Cntr=0.3,0.1

Type RM Length L Ch R = 1,269000,500,500,500
BEGIN DESCRIPTION:
Sweetwater Creek 536.0
END DESCRIPTION:
XS GIS Cut Line= 3
      1370405.04      6822887.97      1370750.81      6822637.25
      1371155.01      6822287.99
#Sta/Elev= 30
  4572.9 2284.37  4583.7 2283.95  4594.9 2279.83  4630.5 2259.71  4666.0 2248.60
  4781.2 2238.65  4816.8 2243.99  4837.7 2244.25  4867.0 2238.27  4873.2 2239.00
  4887.9 2233.44  4906.7 2232.78  4923.5 2231.55  4959.0 2224.96  4967.6 2220.65
  4973.7 2221.78  4983.3 2218.80  4983.9 2217.80  5007.4 2218.80  5009.3 2224.64
  5017.0 2229.78  5123.4 2240.21  5215.5 2245.31  5300.0 2247.10  5363.6 2245.85
  5449.2 2249.69  5470.0 2254.72  5498.5 2267.23  5512.8 2270.12  5534.2 2270.91
#Mann=5,-1,0
  4572.9    0.07       0  4583.7   0.035       0  4906.7    0.07       0
  4983.3    0.07       0  5007.4    0.07       0
Bank Sta=4983.3,5007.4
Exp/Cntr=0.3,0.1

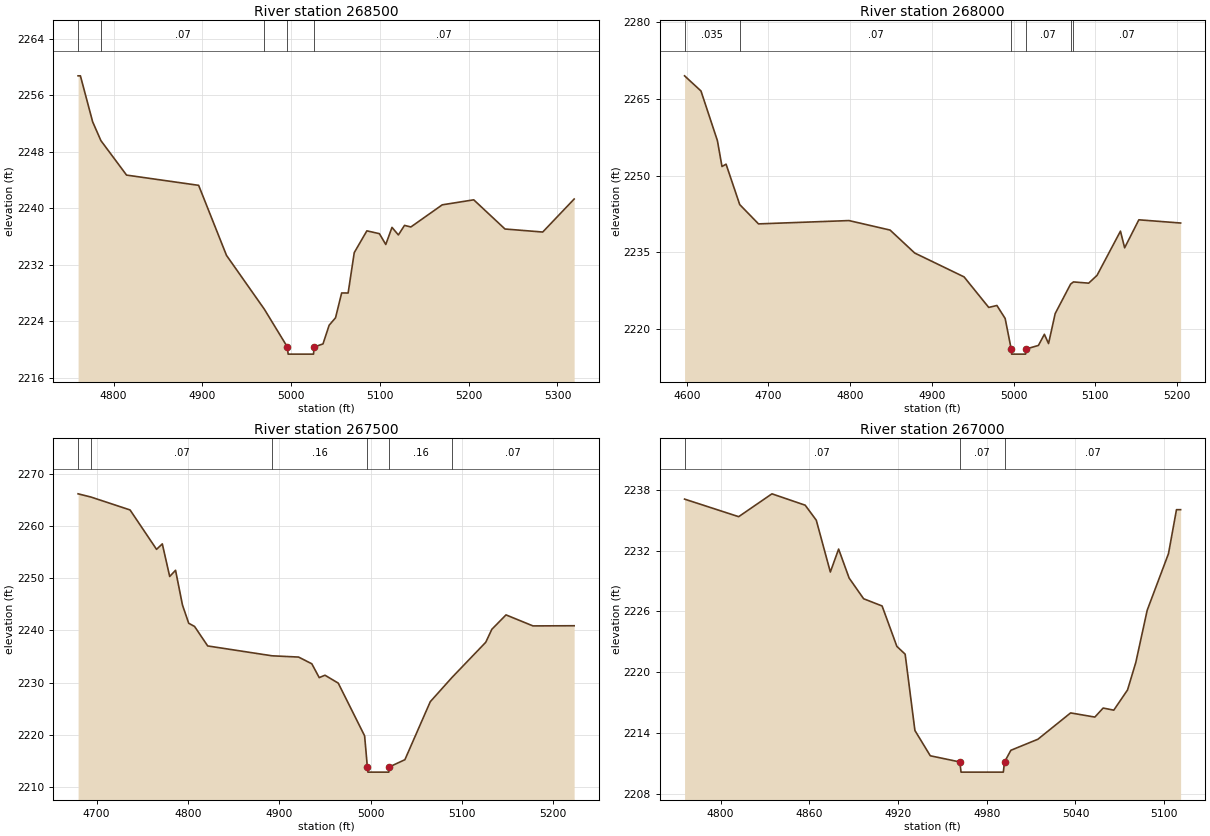
Type RM Length L Ch R = 1,268500,500,500,500
BEGIN DESCRIPTION:
Sweetwater Creek 535.0
END DESCRIPTION:
XS GIS Cut Line= 3
      1370805.01      6823287.98      1370874.60      6823058.29
      1371105.02      6822837.98
#Sta/Elev= 30
  4760.0 2258.74  4762.6 2258.74  4776.4 2252.23  4785.7 2249.57  4814.6 2244.69
  4895.8 2243.24  4927.2 2233.32  4969.8 2225.71  4995.8 2220.35  4996.6 2219.35
  5025.2 2219.35  5025.9 2220.35  5035.9 2220.80  5042.8 2223.44  5050.0 2224.49
  5056.9 2228.01  5064.2 2228.00  5071.1 2233.72  5085.3 2236.80  5099.4 2236.40
  5106.6 2234.87  5113.6 2237.29  5120.8 2236.22  5127.7 2237.57  5134.9 2237.35
  5170.2 2240.48  5205.7 2241.19  5240.9 2237.06  5283.4 2236.63  5318.8 2241.30
#Mann=5,-1,0
  4760.0   0.035       0  4785.7    0.07       0  4969.8    0.16       0
  4995.8    0.07       0  5025.9    0.07       0
Bank Sta=4995.8,5025.9
Exp/Cntr=0.3,0.1

Type RM Length L Ch R = 1,268000,500,500,500
BEGIN DESCRIPTION:
Sweetwater Creek 534.0
END DESCRIPTION:
XS GIS Cut Line= 3
      1371305.00      6823538.00      1371348.43      6823137.65
      1371305.00      6822938.02
#Sta/Elev= 30
  4597.3 2269.55  4617.4 2266.58  4637.5 2256.86  4643.1 2251.80  4648.1 2252.26
  4664.8 2244.35  4687.8 2240.57  4798.5 2241.22  4848.8 2239.36  4878.9 2234.87
  4939.3 2230.20  4969.5 2224.22  4979.5 2224.60  4989.6 2222.06  4997.0 2216.08
  4997.5 2215.08  5014.6 2215.08  5015.1 2216.08  5030.3 2216.78  5037.6 2218.96
  5042.7 2217.15  5050.8 2223.01  5069.7 2228.79  5073.2 2229.21  5091.8 2228.97
  5102.0 2230.49  5130.7 2239.15  5135.8 2235.89  5153.2 2241.37  5204.3 2240.74
#Mann=6,-1,0
  4597.3   0.035       0  4664.8    0.07       0  4997.0    0.07       0
  5015.1    0.07       0  5069.7    0.16       0  5073.2    0.07       0
Bank Sta=4997,5015.1
Exp/Cntr=0.3,0.1

Type RM Length L Ch R = 1,267500,500,500,500
BEGIN DESCRIPTION:
Sweetwater Creek 533.0
END DESCRIPTION:
XS GIS Cut Line= 3
      1371555.01      6823637.98      1371752.48      6823385.80
      1371855.01      6823187.99
#Sta/Elev= 30
  4679.7 2266.16  4693.7 2265.55  4736.6 2263.07  4765.6 2255.52  4771.9 2256.57
  4780.0 2250.32  4786.4 2251.51  4794.0 2244.84  4800.8 2241.36  4807.2 2240.75
  4821.6 2237.01  4892.1 2235.12  4921.1 2234.88  4935.6 2233.59  4943.7 2230.94
  4950.0 2231.40  4964.5 2229.89  4993.4 2219.78  4996.4 2213.83  4997.0 2212.83
  5019.9 2212.83  5020.5 2213.83  5037.5 2215.21  5065.3 2226.33  5088.9 2230.94
  5126.0 2237.71  5132.7 2240.20  5148.2 2242.96  5177.7 2240.85  5222.8 2240.88
#Mann=6,-1,0
  4679.7   0.035       0  4693.7    0.07       0  4892.1    0.16       0
  4996.4    0.07       0  5020.5    0.16       0  5088.9    0.07       0
Bank Sta=4996.4,5020.5
Exp/Cntr=0.3,0.1

Type RM Length L Ch R = 1,267000,500,500,500
BEGIN DESCRIPTION:
Sweetwater Creek 532.0
END DESCRIPTION:
XS GIS Cut Line= 3
      1371854.96      6823838.02      1372056.60      6823739.53
      1372155.02      6823687.99
#Sta/Elev= 30
  4775.6 2237.06  4812.2 2235.33  4834.7 2237.58  4857.2 2236.46  4864.7 2234.98
  4874.2 2229.88  4879.8 2232.14  4886.9 2229.29  4896.7 2227.25  4909.2 2226.54
  4919.2 2222.56  4924.8 2221.79  4931.4 2214.28  4941.8 2211.79  4961.8 2211.18
  4962.6 2210.18  4991.2 2210.18  4992.0 2211.18  4996.3 2212.33  5014.6 2213.42
  5036.7 2216.01  5053.1 2215.60  5058.7 2216.49  5065.9 2216.28  5075.2 2218.27
  5080.8 2220.98  5088.5 2226.12  5102.9 2231.69  5108.3 2236.02  5111.1 2236.02
#Mann=3,-1,0
  4775.6    0.07       0  4961.8    0.07       0  4992.0    0.07       0
Bank Sta=4961.8,4992
Exp/Cntr=0.3,0.1