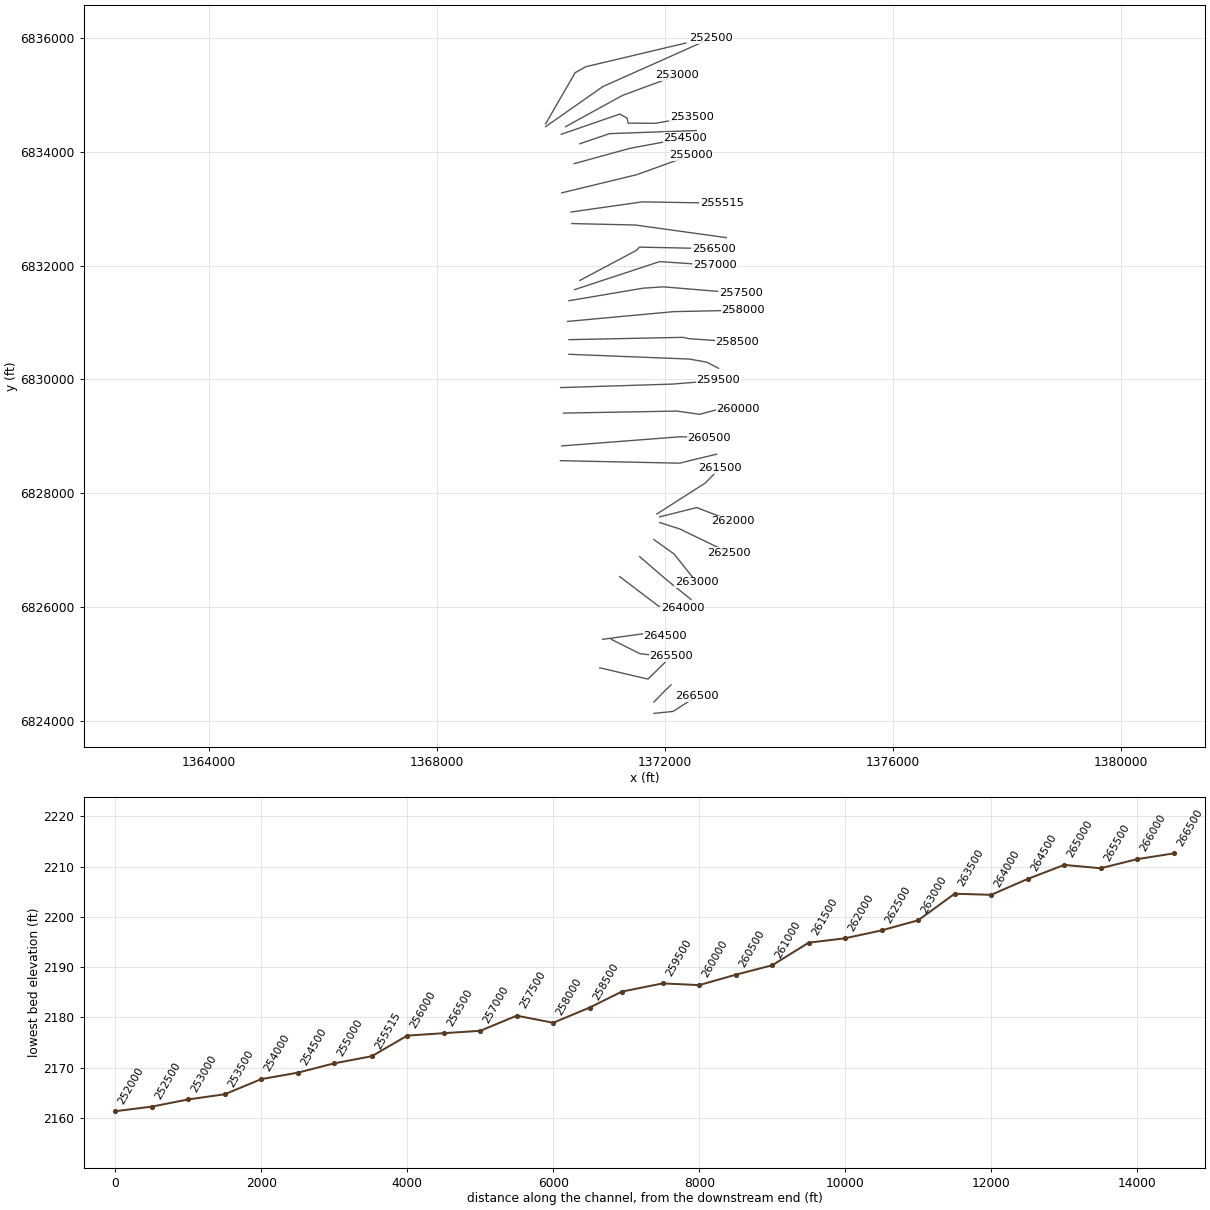
HEC-RAS study Sweetwater Creek.prj: Sweetwater Creek Base Level Engineering

--- Sweetwater Creek.g01 (geometry) --- (continued)

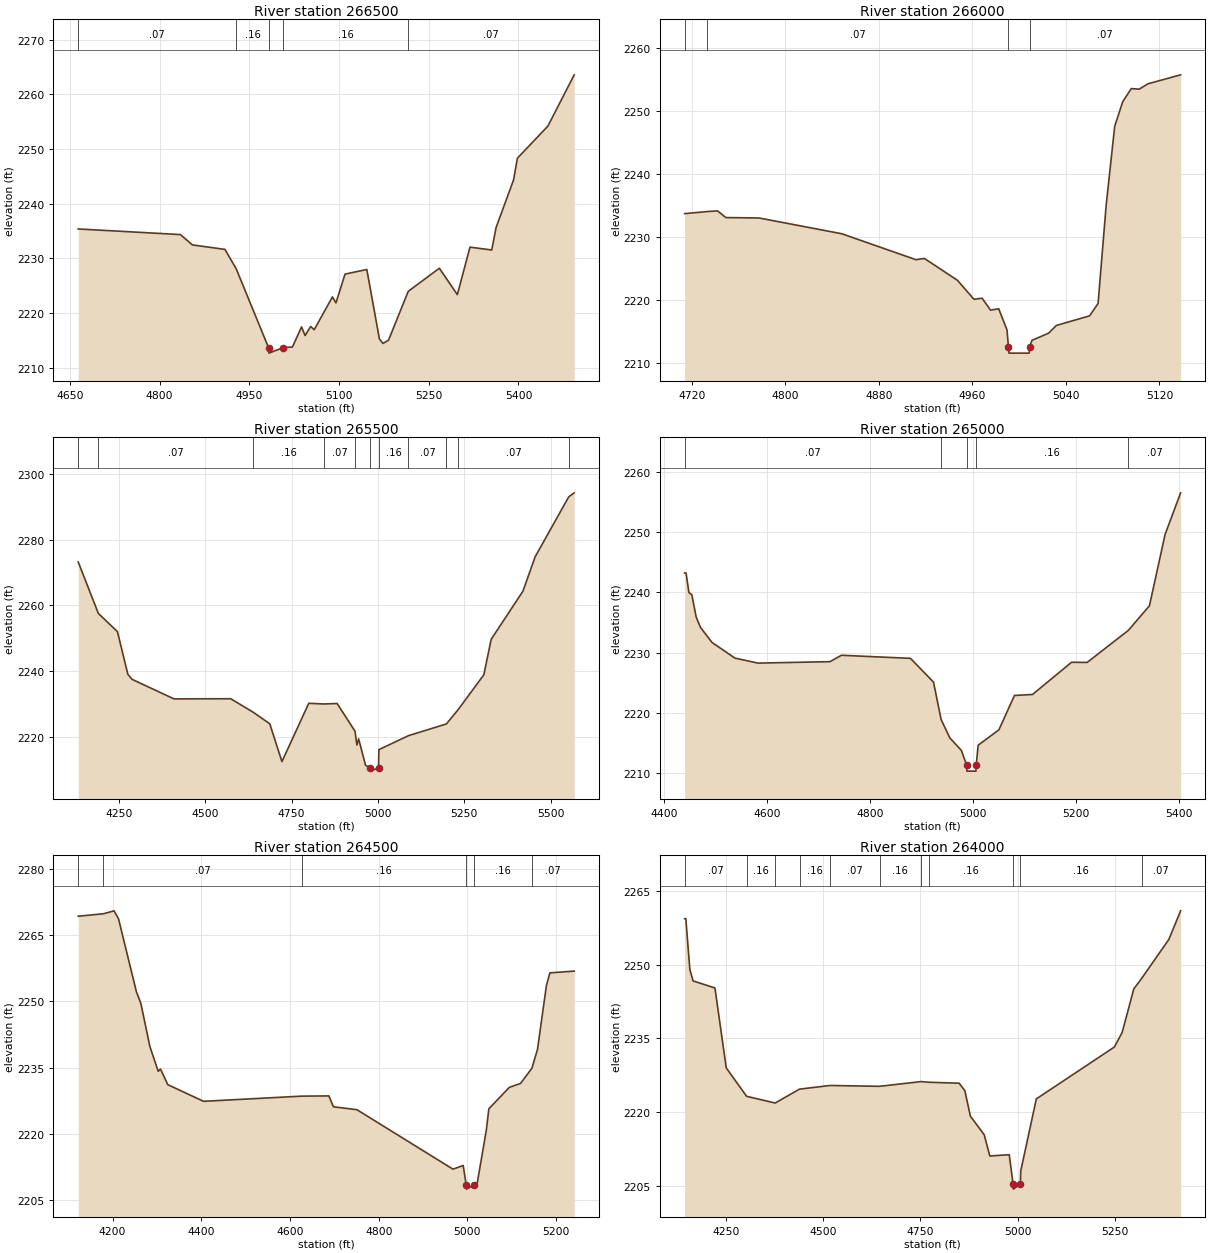
Type RM Length L Ch R = 1,266500,500,500,500
BEGIN DESCRIPTION:
Sweetwater Creek 531.0
END DESCRIPTION:
XS GIS Cut Line= 3
      1371805.03      6824138.00      1372139.47      6824172.37
      1372555.02      6824438.01
#Sta/Elev= 30
  4663.8 2235.36  4834.7 2234.33  4854.8 2232.44  4909.2 2231.62  4928.1 2228.04
  4982.1 2213.64  4982.7 2212.64  5006.2 2213.64  5022.0 2213.76  5037.3 2217.44
  5043.2 2215.86  5052.5 2217.52  5058.4 2216.92  5088.9 2222.92  5094.8 2221.84
  5110.0 2227.10  5146.4 2227.94  5167.5 2215.22  5173.5 2214.42  5182.7 2215.01
  5215.7 2223.95  5267.7 2228.17  5297.8 2223.34  5318.9 2232.03  5355.3 2231.51
  5362.6 2235.63  5391.7 2244.30  5398.2 2248.30  5449.2 2254.18  5493.2 2263.56
#Mann=5,-1,0
  4663.8    0.07       0  4928.1    0.16       0  4982.1    0.07       0
  5006.2    0.16       0  5215.7    0.07       0
Bank Sta=4982.1,5006.2
Exp/Cntr=0.3,0.1

Type RM Length L Ch R = 1,266000,500,500,500
BEGIN DESCRIPTION:
Sweetwater Creek 530.0
END DESCRIPTION:
XS GIS Cut Line= 3
      1371805.02      6824338.02      1372004.34      6824543.40
      1372104.98      6824637.98
#Sta/Elev= 30
  4713.8 2233.70  4733.0 2234.03  4742.0 2234.14  4749.1 2233.07  4777.4 2233.01
  4848.2 2230.50  4911.7 2226.37  4918.9 2226.57  4947.2 2223.09  4961.3 2220.07
  4968.3 2220.24  4975.5 2218.34  4982.5 2218.56  4989.6 2215.18  4990.8 2212.50
  4991.3 2211.50  5008.6 2211.50  5009.0 2212.50  5010.9 2213.53  5025.1 2214.67
  5031.9 2215.91  5060.2 2217.43  5067.5 2219.40  5074.4 2235.00  5081.7 2247.59
  5088.6 2251.52  5095.9 2253.60  5102.7 2253.51  5110.0 2254.35  5138.1 2255.79
#Mann=4,-1,0
  4713.8   0.035       0  4733.0    0.07       0  4990.8    0.07       0
  5009.0    0.07       0
Bank Sta=4990.8,5009
Exp/Cntr=0.3,0.1

Type RM Length L Ch R = 1,265500,500,500,500
BEGIN DESCRIPTION:
Sweetwater Creek 529.0
END DESCRIPTION:
XS GIS Cut Line= 3
      1370855.05      6824937.99      1371699.87      6824739.18
      1372105.00      6825138.00
#Sta/Elev= 30
  4132.1 2273.20  4190.5 2257.58  4245.7 2252.04  4275.9 2239.09  4288.1 2237.56
  4409.4 2231.63  4573.8 2231.67  4638.4 2227.60  4686.8 2224.07  4722.1 2212.58
  4799.8 2230.29  4843.1 2230.08  4882.0 2230.22  4933.8 2221.80  4939.1 2217.62
  4944.2 2219.49  4964.2 2211.47  4977.6 2210.69  4978.2 2209.69  5001.9 2210.69
  5002.8 2216.21  5088.5 2220.46  5198.3 2224.02  5232.1 2228.32  5306.8 2238.95
  5328.1 2249.73  5420.0 2264.33  5455.4 2274.77  5552.6 2292.98  5568.5 2294.20
#Mann=11,-1,0
  4132.1   0.035       0  4190.5    0.07       0  4638.4    0.16       0
  4843.1    0.07       0  4933.8    0.16       0  4977.6    0.07       0
  5001.9    0.16       0  5088.5    0.07       0  5198.3    0.16       0
  5232.1    0.07       0  5552.6   0.035       0
Bank Sta=4977.6,5001.9
Exp/Cntr=0.3,0.1

Type RM Length L Ch R = 1,265000,500,500,500
BEGIN DESCRIPTION:
Sweetwater Creek 528.0
END DESCRIPTION:
XS GIS Cut Line= 3
      1371054.97      6825438.01      1371554.91      6825187.04
      1371955.02      6825138.00
#Sta/Elev= 30
  4440.6 2243.18  4443.4 2243.18  4449.0 2239.93  4454.6 2239.58  4463.0 2235.90
  4471.3 2234.18  4493.7 2231.68  4538.3 2229.08  4583.0 2228.25  4722.6 2228.49
  4744.9 2229.55  4878.9 2229.04  4923.6 2225.10  4938.4 2218.89  4955.3 2215.85
  4977.7 2213.78  4987.9 2211.35  4988.4 2210.35  5006.0 2210.35  5006.5 2211.35
  5010.2 2214.64  5050.5 2217.20  5080.7 2222.89  5115.7 2223.05  5191.5 2228.39
  5221.7 2228.36  5301.6 2233.67  5342.6 2237.75  5372.9 2249.55  5403.1 2256.47
#Mann=5,-1,0
  4440.6    0.07       0  4938.4    0.16       0  4987.9    0.07       0
  5006.5    0.16       0  5301.6    0.07       0
Bank Sta=4987.9,5006.5
Exp/Cntr=0.3,0.1

Type RM Length L Ch R = 1,264500,500,500,500
BEGIN DESCRIPTION:
Sweetwater Creek 527.0
END DESCRIPTION:
XS GIS Cut Line= 3
      1370904.99      6825438.00      1371774.36      6825557.12
      1372005.03      6825487.99
#Sta/Elev= 30
  4122.5 2269.25  4179.5 2269.81  4203.3 2270.47  4213.4 2268.67  4253.7 2252.17
  4263.8 2249.53  4284.0 2239.83  4302.9 2234.18  4308.0 2234.71  4324.4 2231.18
  4405.1 2227.41  4626.4 2228.58  4687.7 2228.63  4697.8 2226.18  4751.0 2225.51
  4967.5 2212.07  4990.5 2212.91  4997.2 2208.56  4997.6 2207.56  5015.7 2208.56
  5021.5 2208.56  5042.4 2220.72  5048.4 2225.73  5094.6 2230.57  5119.8 2231.45
  5145.5 2234.90  5158.1 2239.19  5178.1 2253.56  5185.9 2256.44  5240.8 2256.85
#Mann=6,-1,0
  4122.5   0.035       0  4179.5    0.07       0  4626.4    0.16       0
  4997.2    0.07       0  5015.7    0.16       0  5145.5    0.07       0
Bank Sta=4997.2,5015.7
Exp/Cntr=0.3,0.1

Type RM Length L Ch R = 1,264000,500,500,500
BEGIN DESCRIPTION:
Sweetwater Creek 526.0
END DESCRIPTION:
XS GIS Cut Line= 3
      1371205.02      6826537.98      1371886.75      6826019.98
      1372305.03      6825988.00
#Sta/Elev= 30
  4143.8 2259.31  4146.9 2259.31  4157.3 2248.98  4165.6 2246.67  4221.8 2245.24
  4250.9 2229.01  4303.2 2223.25  4376.6 2221.88  4439.3 2224.70  4518.0 2225.44
  4645.1 2225.27  4751.6 2226.23  4772.2 2226.10  4849.8 2225.90  4864.4 2224.42
  4878.9 2219.20  4914.3 2215.45  4928.8 2211.13  4978.7 2211.39  4988.7 2205.40
  4989.2 2204.40  5007.3 2205.40  5008.3 2208.09  5048.4 2222.72  5249.0 2233.24
  5269.0 2236.18  5299.1 2245.04  5319.2 2247.17  5389.4 2255.11  5419.5 2260.90
#Mann=11,-1,0
  4143.8    0.07       0  4303.2    0.16       0  4376.6    0.07       0
  4439.3    0.16       0  4518.0    0.07       0  4645.1    0.16       0
  4751.6    0.07       0  4772.2    0.16       0  4988.7    0.07       0
  5007.3    0.16       0  5319.2    0.07       0
Bank Sta=4988.7,5007.3
Exp/Cntr=0.3,0.1

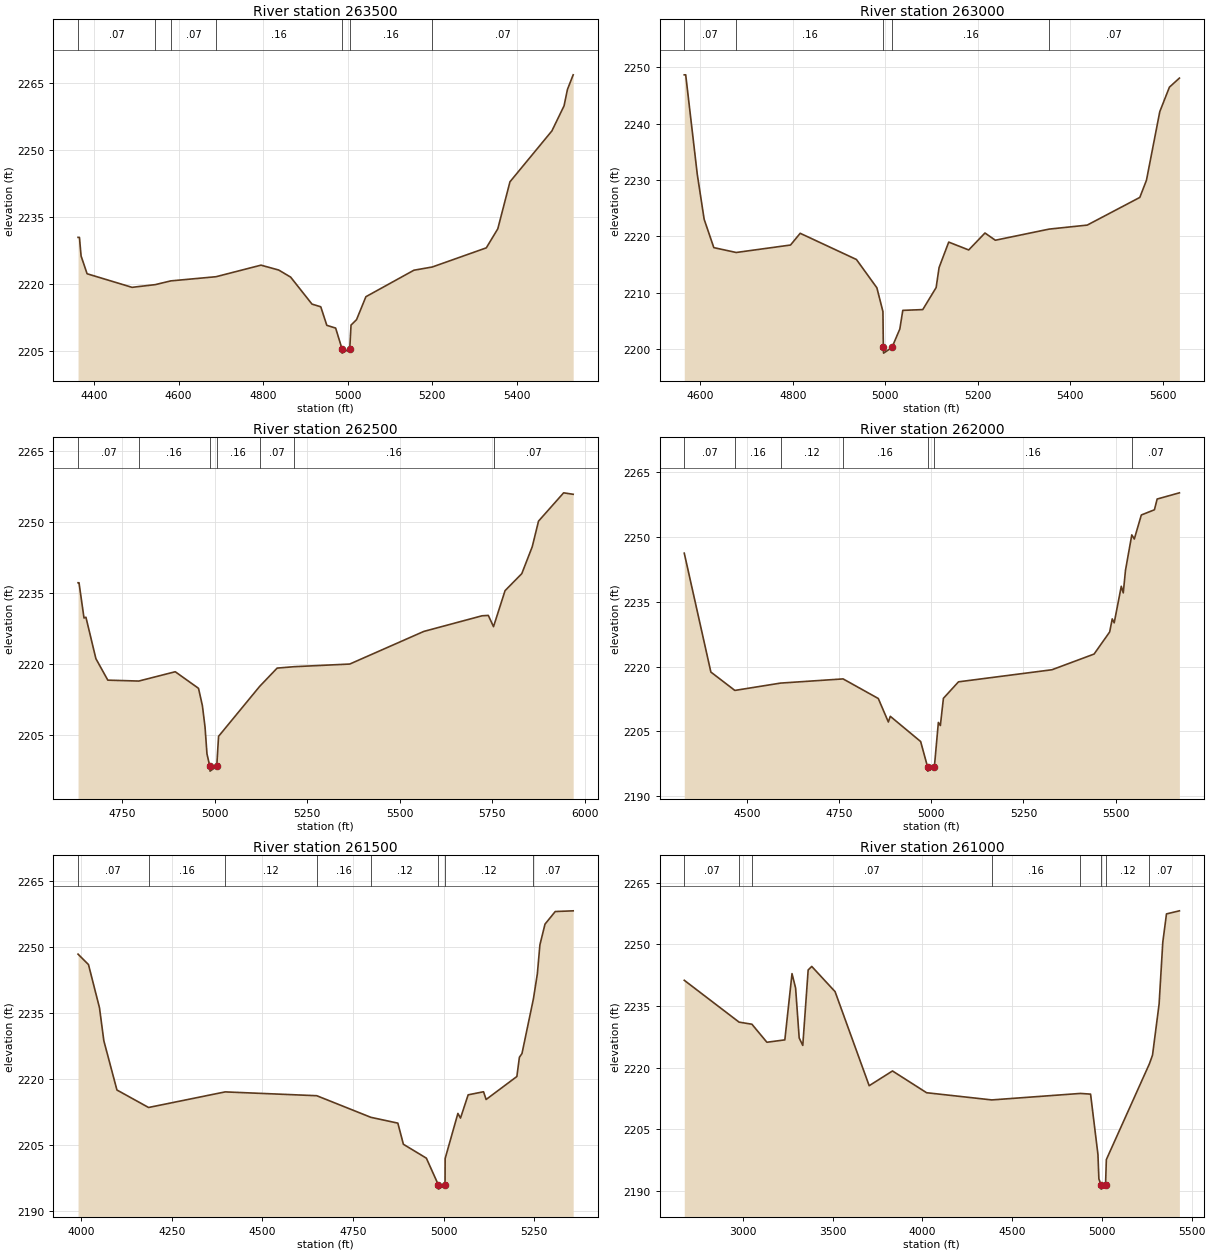
Type RM Length L Ch R = 1,263500,500,500,500
BEGIN DESCRIPTION:
Sweetwater Creek 525.0
END DESCRIPTION:
XS GIS Cut Line= 3
      1371554.99      6826888.01      1372038.62      6826471.91
      1372454.98      6826138.02
#Sta/Elev= 30
  4362.0 2230.45  4365.3 2230.45  4369.2 2226.30  4383.4 2222.33  4489.8 2219.30
  4544.5 2219.90  4581.6 2220.74  4688.5 2221.67  4794.9 2224.25  4836.9 2223.16
  4865.1 2221.58  4915.6 2215.56  4936.4 2214.96  4950.7 2210.82  4971.6 2210.21
  4986.5 2205.62  4986.9 2204.62  5005.0 2205.62  5008.0 2210.88  5021.0 2212.08
  5043.2 2217.21  5156.8 2223.12  5200.3 2223.84  5328.1 2228.11  5355.3 2232.36
  5384.1 2242.85  5483.3 2254.20  5512.1 2259.80  5520.1 2263.45  5533.7 2266.72
#Mann=7,-1,0
  4362.0    0.07       0  4544.5    0.16       0  4581.6    0.07       0
  4688.5    0.16       0  4986.5    0.07       0  5005.0    0.16       0
  5200.3    0.07       0
Bank Sta=4986.5,5005
Exp/Cntr=0.3,0.1

Type RM Length L Ch R = 1,263000,500,500,500
BEGIN DESCRIPTION:
Sweetwater Creek 524.0
END DESCRIPTION:
XS GIS Cut Line= 3
      1371805.01      6827187.99      1372158.31      6826934.91
      1372554.98      6826438.02
#Sta/Elev= 30
  4565.4 2248.62  4568.5 2248.62  4593.6 2230.96  4608.4 2223.04  4629.3 2218.02
  4677.7 2217.16  4795.1 2218.48  4816.0 2220.56  4937.6 2215.92  4981.8 2210.91
  4994.9 2206.69  4995.8 2200.34  4996.3 2199.34  5014.4 2200.34  5031.4 2203.61
  5037.8 2206.91  5081.0 2207.05  5109.9 2210.95  5116.3 2214.50  5137.1 2219.00
  5180.3 2217.61  5215.5 2220.61  5237.9 2219.33  5354.1 2221.30  5436.5 2222.01
  5550.2 2226.91  5564.6 2229.96  5593.4 2242.10  5614.2 2246.43  5635.8 2248.04
#Mann=5,-1,0
  4565.4    0.07       0  4677.7    0.16       0  4995.8    0.07       0
  5014.4    0.16       0  5354.1    0.07       0
Bank Sta=4995.8,5014.4
Exp/Cntr=0.3,0.1

Type RM Length L Ch R = 1,262500,500,500,500
BEGIN DESCRIPTION:
Sweetwater Creek 523.0
END DESCRIPTION:
XS GIS Cut Line= 3
      1371905.01      6827488.00      1372256.39      6827375.65
      1373128.27      6826954.19
#Sta/Elev= 30
  4631.1 2237.19  4633.7 2237.19  4647.2 2229.73  4652.4 2229.89  4679.3 2221.13
  4711.5 2216.58  4795.2 2216.39  4893.6 2218.36  4956.5 2214.85  4967.0 2211.16
  4974.1 2206.64  4979.3 2200.99  4987.1 2198.33  4987.6 2197.33  5005.7 2198.33
  5010.6 2204.69  5121.6 2215.26  5168.8 2219.13  5214.9 2219.43  5365.0 2219.99
  5564.9 2226.89  5722.2 2230.20  5739.2 2230.28  5753.2 2227.90  5784.4 2235.52
  5829.6 2239.12  5857.8 2244.81  5874.8 2250.23  5942.6 2256.22  5968.4 2255.91
#Mann=7,-1,0
  4631.1    0.07       0  4795.2    0.16       0  4987.1    0.07       0
  5005.7    0.16       0  5121.6    0.07       0  5214.9    0.16       0
  5753.2    0.07       0
Bank Sta=4987.1,5005.7
Exp/Cntr=0.3,0.1

Type RM Length L Ch R = 1,262000,500,500,500
BEGIN DESCRIPTION:
Sweetwater Creek 522.0
END DESCRIPTION:
XS GIS Cut Line= 3
      1371905.03      6827588.01      1372554.11      6827750.88
      1373181.25      6827507.80
#Sta/Elev= 30
  4330.8 2246.29  4402.9 2218.73  4467.9 2214.47  4591.8 2216.17  4761.2 2217.14
  4856.6 2212.60  4883.9 2207.15  4889.1 2208.47  4971.4 2202.62  4990.1 2196.76
  4990.5 2195.76  5008.6 2196.76  5019.4 2207.05  5024.8 2206.33  5033.1 2212.64
  5073.9 2216.46  5327.1 2219.26  5441.4 2222.90  5483.6 2228.02  5490.6 2231.05
  5495.9 2230.14  5515.1 2238.61  5520.5 2237.08  5526.5 2242.33  5543.6 2250.53
  5550.4 2249.57  5569.4 2255.14  5604.9 2256.35  5612.3 2258.84  5672.6 2260.28
#Mann=7,-1,0
  4330.8    0.07       0  4467.9    0.16       0  4591.8    0.12       0
  4761.2    0.16       0  4990.1    0.07       0  5008.6    0.16       0
  5543.6    0.07       0
Bank Sta=4990.1,5008.6
Exp/Cntr=0.3,0.1

Type RM Length L Ch R = 1,261500,500,500,500
BEGIN DESCRIPTION:
Sweetwater Creek 521.0
END DESCRIPTION:
XS GIS Cut Line= 3
      1371854.99      6827637.99      1372705.18      6828181.57
      1372954.99      6828437.99
#Sta/Elev= 30
  3990.9 2248.36  4019.7 2245.99  4050.1 2236.16  4062.1 2228.65  4098.3 2217.44
  4185.6 2213.46  4397.1 2217.01  4650.0 2216.14  4799.5 2211.22  4873.9 2209.90
  4889.2 2205.09  4952.6 2201.93  4985.6 2195.88  4986.1 2194.88  5004.2 2195.88
  5004.5 2201.85  5039.7 2212.11  5046.9 2211.05  5068.0 2216.34  5110.5 2217.04
  5117.6 2215.28  5202.5 2220.51  5209.5 2224.89  5216.6 2225.73  5248.2 2238.19
  5259.1 2243.90  5266.1 2250.47  5280.2 2255.19  5308.5 2258.06  5358.0 2258.22
#Mann=8,-1,0
  3990.9    0.07       0  4185.6    0.16       0  4397.1    0.12       0
  4650.0    0.16       0  4799.5    0.12       0  4985.6    0.07       0
  5004.2    0.12       0  5248.2    0.07       0
Bank Sta=4985.6,5004.2
Exp/Cntr=0.3,0.1

Type RM Length L Ch R = 1,261000,500,500,500
BEGIN DESCRIPTION:
Sweetwater Creek 520.0
END DESCRIPTION:
XS GIS Cut Line= 4
      1370164.54      6828573.98      1372257.53      6828530.23
      1372484.89      6828587.46      1372905.03      6828688.01
#Sta/Elev= 30
  2672.1 2241.24  2977.7 2231.05  3049.2 2230.54  3132.7 2226.15  3232.7 2226.73
  3272.7 2242.86  3292.7 2239.35  3312.7 2227.19  3332.7 2225.38  3362.7 2243.75
  3382.7 2244.61  3512.7 2238.48  3702.8 2215.57  3832.8 2219.16  4022.9 2213.86
  4386.4 2212.11  4880.4 2213.69  4936.9 2213.52  4978.0 2198.81  4983.2 2192.89
  4995.5 2191.39  4996.1 2190.39  5020.3 2191.39  5024.8 2197.58  5264.7 2220.89
  5282.2 2223.02  5318.9 2235.48  5339.4 2250.49  5360.0 2257.40  5432.0 2258.15
#Mann=8,-1,0
  2672.1    0.07       0  2977.7   0.035       0  3049.2    0.07       0
  4386.4    0.16       0  4880.4    0.12       0  4995.5    0.07       0
  5020.3    0.12       0  5264.7    0.07       0
Bank Sta=4995.5,5020.3
Exp/Cntr=0.3,0.1

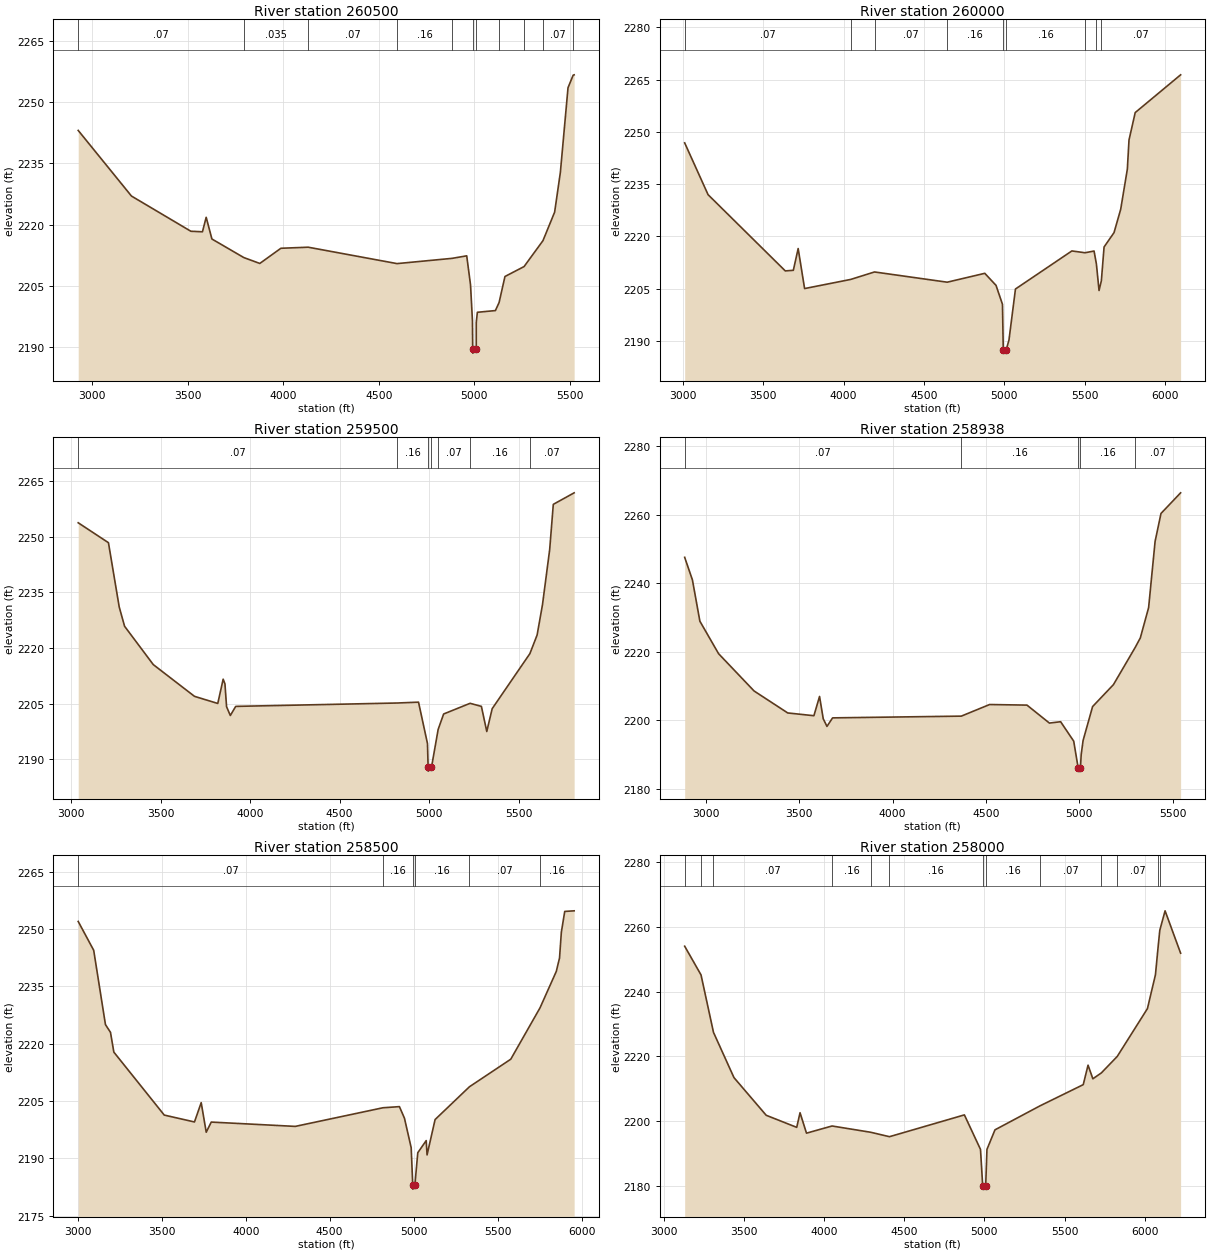
Type RM Length L Ch R = 1,260500,500,500,500
BEGIN DESCRIPTION:
Sweetwater Creek 519.0
END DESCRIPTION:
XS GIS Cut Line= 3
      1370186.98      6828833.30      1372271.37      6828994.15
      1372777.12      6828977.82
#Sta/Elev= 30
  2926.3 2243.09  3205.1 2227.01  3516.1 2218.38  3576.8 2218.25  3596.3 2221.80
  3626.4 2216.48  3793.4 2211.93  3877.1 2210.49  3987.5 2214.21  4130.5 2214.47
  4595.6 2210.45  4884.2 2211.74  4960.4 2212.36  4980.4 2205.22  4990.4 2196.45
  4991.8 2189.51  4992.3 2188.51  5010.4 2189.51  5010.5 2196.08  5016.2 2198.52
  5110.6 2198.94  5129.9 2200.91  5160.6 2207.29  5260.6 2209.72  5359.7 2216.08
  5420.7 2223.06  5450.7 2232.79  5490.8 2253.55  5517.7 2256.64  5522.9 2256.72
#Mann=11,-1,0
  2926.3    0.07       0  3793.4   0.035       0  4130.5    0.07       0
  4595.6    0.16       0  4884.2    0.12       0  4991.8    0.07       0
  5010.4    0.12       0  5129.9    0.16       0  5260.6    0.12       0
  5359.7    0.07       0  5517.7    0.16       0
Bank Sta=4991.8,5010.4
Exp/Cntr=0.3,0.1

Type RM Length L Ch R = 1,260000,500,500,500
BEGIN DESCRIPTION:
Sweetwater Creek 518.0
END DESCRIPTION:
XS GIS Cut Line= 5
      1370219.64      6829409.32      1372207.13      6829444.56
      1372605.00      6829388.00      1372998.12      6829493.24
      1373284.40      6829482.79
#Sta/Elev= 30
  3012.2 2246.85  3157.6 2231.97  3637.7 2210.06  3687.7 2210.24  3717.7 2216.49
  3757.7 2204.99  4044.0 2207.61  4192.3 2209.76  4644.3 2206.82  4877.9 2209.37
  4947.9 2205.90  4987.9 2200.45  4992.8 2187.44  4993.3 2186.44  5011.4 2187.44
  5028.2 2190.20  5068.6 2204.86  5419.3 2215.80  5500.9 2215.28  5557.2 2215.77
  5571.9 2212.02  5588.2 2204.43  5602.6 2207.23  5619.5 2216.94  5681.4 2221.07
  5722.8 2227.76  5764.1 2239.29  5774.5 2247.68  5813.0 2255.55  6095.3 2266.40
#Mann=9,-1,0
  3012.2    0.07       0  4044.0   0.035       0  4192.3    0.07       0
  4644.3    0.16       0  4992.8    0.07       0  5011.4    0.16       0
  5500.9    0.07       0  5571.9    0.16       0  5602.6    0.07       0
Bank Sta=4992.8,5011.4
Exp/Cntr=0.3,0.1

Type RM Length L Ch R = 1,259500,562,562,562
BEGIN DESCRIPTION:
Sweetwater Creek 517.0
END DESCRIPTION:
XS GIS Cut Line= 3
      1370166.26      6829857.06      1372124.81      6829918.14
      1372931.13      6829982.67
#Sta/Elev= 30
  3040.5 2253.76  3209.3 2248.39  3269.4 2231.05  3299.4 2225.85  3459.4 2215.52
  3689.6 2206.95  3819.6 2205.03  3849.6 2211.58  3859.6 2210.32  3868.7 2204.14
  3889.7 2201.79  3919.7 2204.24  4820.7 2205.15  4940.2 2205.38  4990.2 2194.20
  4993.8 2187.78  4994.2 2186.78  5012.4 2187.78  5049.8 2198.04  5080.4 2202.19
  5228.0 2205.07  5291.1 2204.24  5321.2 2197.47  5351.3 2203.62  5561.8 2218.47
  5602.1 2223.48  5632.2 2231.69  5672.3 2246.54  5692.5 2258.73  5808.9 2261.84
#Mann=7,-1,0
  3040.5    0.07       0  4820.7    0.16       0  4993.8    0.07       0
  5012.4    0.16       0  5049.8    0.07       0  5228.0    0.16       0
  5561.8    0.07       0
Bank Sta=4993.8,5012.4
Exp/Cntr=0.3,0.1

Type RM Length L Ch R = 1,258938,438,438,438
BEGIN DESCRIPTION:
Sweetwater Creek 516.0
END DESCRIPTION:
XS GIS Cut Line= 4
      1370313.65      6830441.35      1372425.50      6830357.80
      1372730.90      6830303.34      1372936.05      6830195.69
#Sta/Elev= 30
  2886.5 2247.61  2927.9 2241.03  2967.9 2228.95  3068.0 2219.46  3258.1 2208.56
  3438.3 2202.14  3578.4 2201.33  3608.6 2206.96  3628.4 2200.43  3648.4 2198.21
  3678.5 2200.70  4367.8 2201.21  4519.1 2204.60  4719.3 2204.43  4839.4 2199.18
  4899.4 2199.58  4969.5 2193.90  4993.2 2186.14  4993.5 2185.14  5005.6 2186.14
  5009.6 2190.01  5019.8 2194.11  5070.6 2204.00  5182.3 2210.42  5298.5 2221.26
  5326.1 2224.06  5370.6 2232.92  5405.2 2252.25  5436.8 2260.43  5541.9 2266.46
#Mann=5,-1,0
  2886.5    0.07       0  4367.8    0.16       0  4993.2    0.07       0
  5005.6    0.16       0  5298.5    0.07       0
Bank Sta=4993.2,5005.6
Exp/Cntr=0.3,0.1

Type RM Length L Ch R = 1,258500,500,500,500
BEGIN DESCRIPTION:
Sweetwater Creek 515.0
END DESCRIPTION:
XS GIS Cut Line= 4
      1370312.82      6830698.48      1372309.61      6830738.79
      1372423.56      6830715.21      1373261.00      6830657.28
#Sta/Elev= 30
  3002.8 2251.96  3095.0 2244.43  3165.0 2225.00  3195.0 2222.97  3215.0 2217.80
  3515.1 2201.34  3695.1 2199.54  3735.1 2204.59  3765.1 2196.86  3795.1 2199.51
  4295.2 2198.38  4817.2 2203.25  4915.4 2203.55  4945.4 2200.52  4985.4 2192.82
  4994.9 2182.98  4995.2 2181.98  5007.3 2182.98  5024.7 2191.49  5074.9 2194.67
  5080.0 2190.93  5127.8 2200.17  5332.3 2208.74  5578.5 2215.95  5752.5 2229.37
  5849.5 2238.90  5868.8 2242.42  5879.6 2249.15  5899.7 2254.58  5955.8 2254.74
#Mann=6,-1,0
  3002.8    0.07       0  4817.2    0.16       0  4994.9    0.07       0
  5007.3    0.16       0  5332.3    0.07       0  5752.5    0.16       0
Bank Sta=4994.9,5007.3
Exp/Cntr=0.3,0.1

Type RM Length L Ch R = 1,258000,500,500,500
BEGIN DESCRIPTION:
Sweetwater Creek 514.0
END DESCRIPTION:
XS GIS Cut Line= 3
      1370289.05      6831018.43      1372149.25      6831190.09
      1373371.77      6831216.17
#Sta/Elev= 30
  3131.9 2254.05  3233.8 2245.18  3311.5 2227.41  3439.1 2213.43  3640.0 2201.78
  3830.2 2198.05  3850.9 2202.57  3891.1 2196.25  4050.3 2198.47  4291.4 2196.53
  4408.3 2195.16  4875.2 2201.90  4975.6 2191.23  4989.3 2179.95  4989.7 2178.95
  5007.9 2179.95  5015.8 2191.23  5065.8 2197.28  5346.6 2204.70  5615.9 2211.25
  5645.9 2217.27  5675.9 2213.06  5728.8 2214.88  5827.8 2219.97  6016.0 2234.76
  6066.0 2245.25  6082.5 2253.80  6093.1 2258.99  6126.0 2264.99  6222.8 2251.90
#Mann=13,-1,0
  3131.9    0.07       0  3233.8    0.16       0  3311.5    0.07       0
  4050.3    0.16       0  4291.4    0.07       0  4408.3    0.16       0
  4989.3    0.07       0  5007.9    0.16       0  5346.6    0.07       0
  5728.8    0.16       0  5827.8    0.07       0  6082.5    0.16       0
  6093.1    0.07       0
Bank Sta=4989.3,5007.9
Exp/Cntr=0.3,0.1

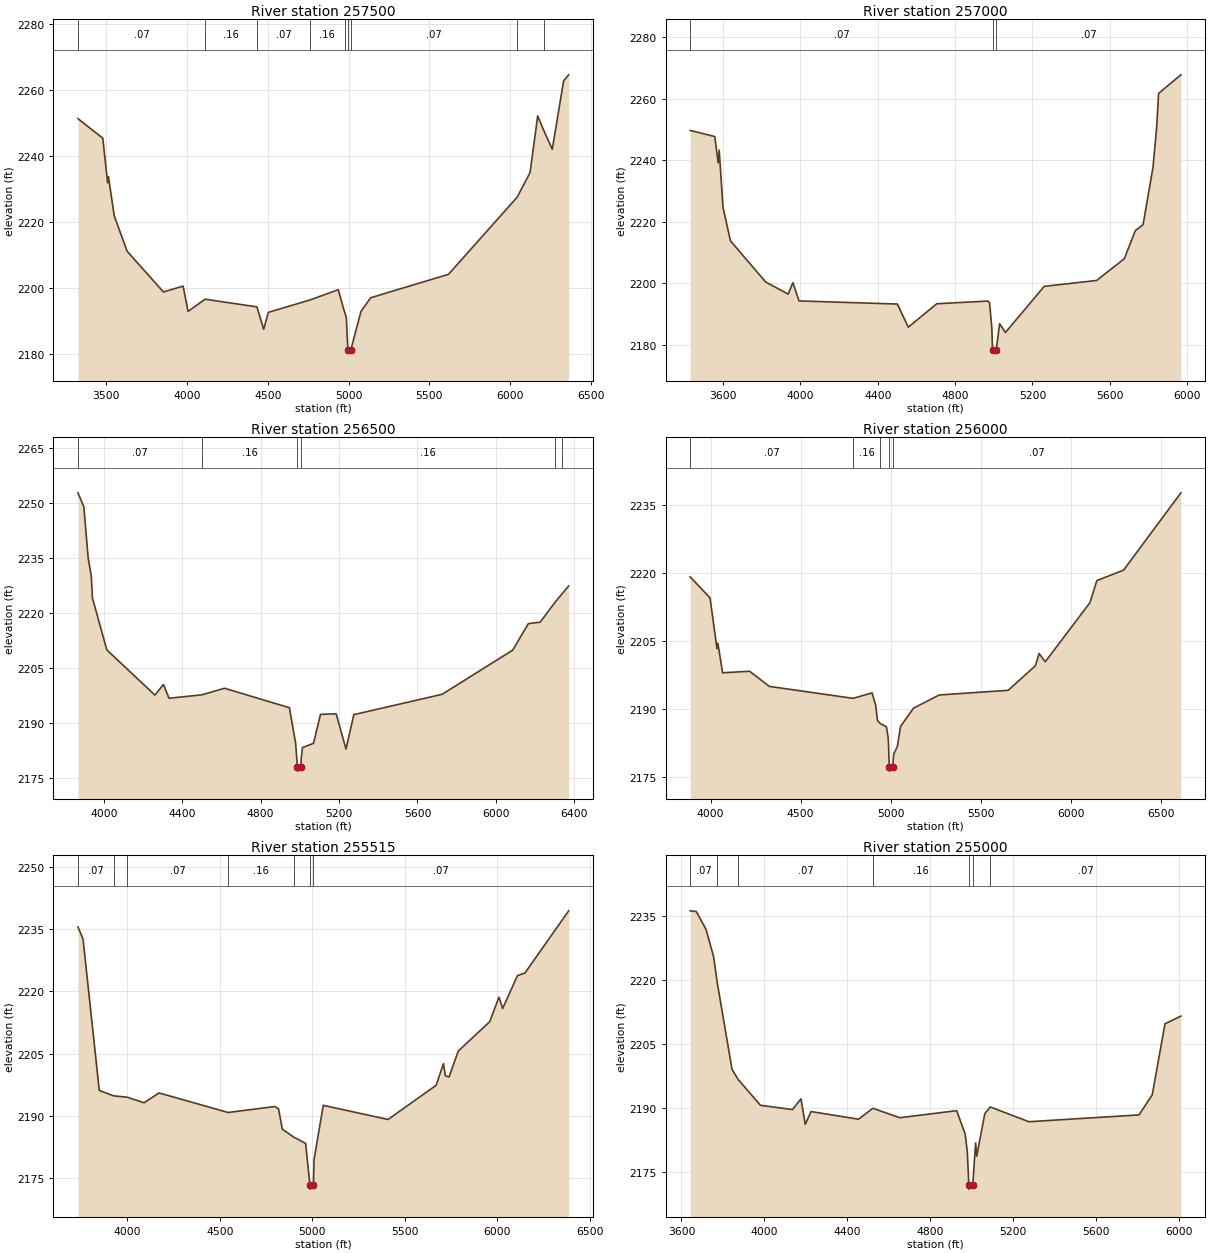
Type RM Length L Ch R = 1,257500,500,500,500
BEGIN DESCRIPTION:
Sweetwater Creek 513.0
END DESCRIPTION:
XS GIS Cut Line= 4
      1370313.38      6831381.62      1371613.22      6831601.81
      1371968.39      6831625.31      1373326.06      6831513.18
#Sta/Elev= 30
  3325.7 2251.37  3479.5 2245.45  3509.2 2231.96  3514.3 2233.79  3550.5 2221.89
  3629.9 2211.22  3854.8 2198.88  3976.5 2200.66  4006.9 2192.99  4112.5 2196.69
  4433.3 2194.36  4475.0 2187.59  4503.9 2192.71  4759.8 2196.43  4936.5 2199.57
  4975.7 2192.73  4986.6 2191.15  4995.7 2181.36  4996.1 2180.36  5014.3 2181.36
  5076.9 2192.97  5137.1 2197.13  5618.7 2204.23  6043.4 2227.58  6123.5 2235.06
  6170.6 2252.21  6206.5 2247.97  6260.9 2242.10  6331.1 2262.83  6362.3 2264.64
#Mann=9,-1,0
  3325.7    0.07       0  4112.5    0.16       0  4433.3    0.07       0
  4759.8    0.16       0  4975.7    0.07       0  4995.7    0.07       0
  5014.3    0.07       0  6043.4    0.16       0  6206.5    0.07       0
Bank Sta=4995.7,5014.3
Exp/Cntr=0.3,0.1

Type RM Length L Ch R = 1,257000,500,500,500
BEGIN DESCRIPTION:
Sweetwater Creek 512.0
END DESCRIPTION:
XS GIS Cut Line= 3
      1370413.95      6831577.09      1371904.59      6832068.67
      1372869.86      6832002.99
#Sta/Elev= 30
  3430.4 2249.66  3557.9 2247.67  3575.3 2239.12  3580.6 2243.28  3600.0 2224.78
  3638.8 2213.80  3821.1 2200.44  3936.9 2196.52  3961.7 2200.22  3993.5 2194.30
  4501.6 2193.28  4558.2 2185.78  4705.6 2193.38  4968.8 2194.25  4978.0 2193.78
  4989.9 2185.74  4993.8 2178.35  4994.3 2177.35  5012.5 2178.35  5030.5 2186.87
  5060.5 2184.05  5261.0 2199.03  5531.6 2200.94  5674.8 2207.97  5732.1 2217.12
  5772.2 2219.08  5823.7 2237.79  5842.4 2250.78  5852.4 2261.67  5967.5 2267.71
#Mann=3,-1,0
  3430.4    0.07       0  4993.8    0.07       0  5012.5    0.07       0
Bank Sta=4993.8,5012.5
Exp/Cntr=0.3,0.1

Type RM Length L Ch R = 1,256500,500,500,500
BEGIN DESCRIPTION:
Sweetwater Creek 511.0
END DESCRIPTION:
XS GIS Cut Line= 4
      1370505.02      6831738.01      1371504.15      6832269.72
      1371549.35      6832322.73      1372850.61      6832295.94
#Sta/Elev= 30
  3868.2 2252.67  3898.3 2248.87  3920.3 2234.91  3936.1 2230.05  3942.2 2223.99
  4015.4 2209.90  4260.5 2197.60  4304.4 2200.47  4332.6 2196.73  4500.5 2197.66
  4615.8 2199.45  4946.6 2194.15  4978.3 2184.54  4987.8 2177.88  4988.2 2176.88
  5006.5 2177.88  5006.7 2180.25  5013.2 2183.29  5069.7 2184.46  5105.3 2192.34
  5185.3 2192.50  5235.4 2182.89  5275.4 2192.26  5725.5 2197.80  6085.5 2209.81
  6165.5 2217.05  6225.6 2217.43  6303.5 2222.99  6335.6 2225.05  6371.2 2227.31
#Mann=6,-1,0
  3868.2    0.07       0  4500.5    0.16       0  4987.8    0.07       0
  5006.5    0.16       0  6303.5    0.16       0  6335.6    0.07       0
Bank Sta=4987.8,5006.5
Exp/Cntr=0.3,0.1

Type RM Length L Ch R = 1,256000,485,485,485
BEGIN DESCRIPTION:
Sweetwater Creek 510.0
END DESCRIPTION:
XS GIS Cut Line= 3
      1370364.78      6832736.51      1371478.09      6832711.00
      1373075.16      6832489.21
#Sta/Elev= 30
  3886.4 2219.18  3996.7 2214.56  4035.6 2203.36  4040.6 2204.56  4066.7 2198.05
  4216.7 2198.39  4326.7 2195.05  4791.4 2192.42  4896.9 2193.63  4917.3 2190.86
  4926.9 2187.57  4941.8 2186.89  4976.9 2186.15  4986.9 2183.63  4992.7 2177.39
  4993.1 2176.39  5011.5 2177.39  5017.1 2180.13  5037.3 2181.81  5055.3 2186.25
  5127.0 2190.25  5269.5 2193.16  5653.1 2194.19  5804.6 2199.62  5824.8 2202.30
  5859.0 2200.47  6107.4 2213.51  6145.7 2218.36  6294.1 2220.66  6612.4 2237.69
#Mann=5,-1,0
  3886.4    0.07       0  4791.4    0.16       0  4941.8    0.07       0
  4992.7    0.07       0  5011.5    0.07       0
Bank Sta=4992.7,5011.5
Exp/Cntr=0.3,0.1

Type RM Length L Ch R = 1,255515,515,515,515
BEGIN DESCRIPTION:
Sweetwater Creek 509.0
END DESCRIPTION:
XS GIS Cut Line= 3
      1370350.90      6832939.36      1371600.51      6833117.37
      1372991.87      6833093.33
#Sta/Elev= 30
  3732.9 2235.55  3760.5 2232.59  3848.2 2196.10  3925.8 2194.80  3999.8 2194.47
  4090.6 2193.13  4171.4 2195.50  4544.9 2190.79  4797.6 2192.22  4817.6 2191.69
  4838.0 2186.77  4899.3 2184.86  4964.2 2183.33  4987.4 2173.30  4987.9 2172.30
  5006.3 2173.30  5009.6 2179.40  5059.6 2192.51  5409.7 2189.10  5669.7 2197.34
  5709.7 2202.55  5719.7 2199.64  5739.7 2199.34  5789.7 2205.61  5959.8 2212.69
  6009.8 2218.62  6029.8 2215.88  6109.8 2223.81  6149.8 2224.42  6386.7 2239.43
#Mann=7,-1,0
  3732.9    0.07       0  3925.8    0.16       0  3999.8    0.07       0
  4544.9    0.16       0  4899.3    0.07       0  4987.4    0.07       0
  5006.3    0.07       0
Bank Sta=4987.4,5006.3
Exp/Cntr=0.3,0.1

Type RM Length L Ch R = 1,255000,500,500,500
BEGIN DESCRIPTION:
Sweetwater Creek 508.0
END DESCRIPTION:
XS GIS Cut Line= 3
      1370185.26      6833274.89      1371504.94      6833595.19
      1372454.99      6833938.00
#Sta/Elev= 30
  3642.0 2236.28  3671.9 2236.12  3718.8 2231.89  3754.9 2225.55  3772.3 2219.53
  3844.2 2199.02  3873.5 2196.66  3981.3 2190.58  4135.7 2189.58  4176.8 2192.09
  4197.4 2186.10  4225.3 2189.11  4454.7 2187.31  4523.6 2189.88  4653.4 2187.66
  4928.0 2189.32  4969.2 2183.80  4979.5 2179.62  4986.9 2171.88  4987.3 2170.88
  5005.7 2171.88  5019.5 2181.74  5024.8 2178.61  5063.8 2188.61  5090.0 2190.19
  5276.5 2186.72  5808.0 2188.32  5871.8 2193.03  5933.3 2209.73  6010.0 2211.54
#Mann=7,-1,0
  3642.0    0.07       0  3772.3    0.16       0  3873.5    0.07       0
  4523.6    0.16       0  4986.9    0.07       0  5005.7    0.16       0
  5090.0    0.07       0
Bank Sta=4986.9,5005.7
Exp/Cntr=0.3,0.1

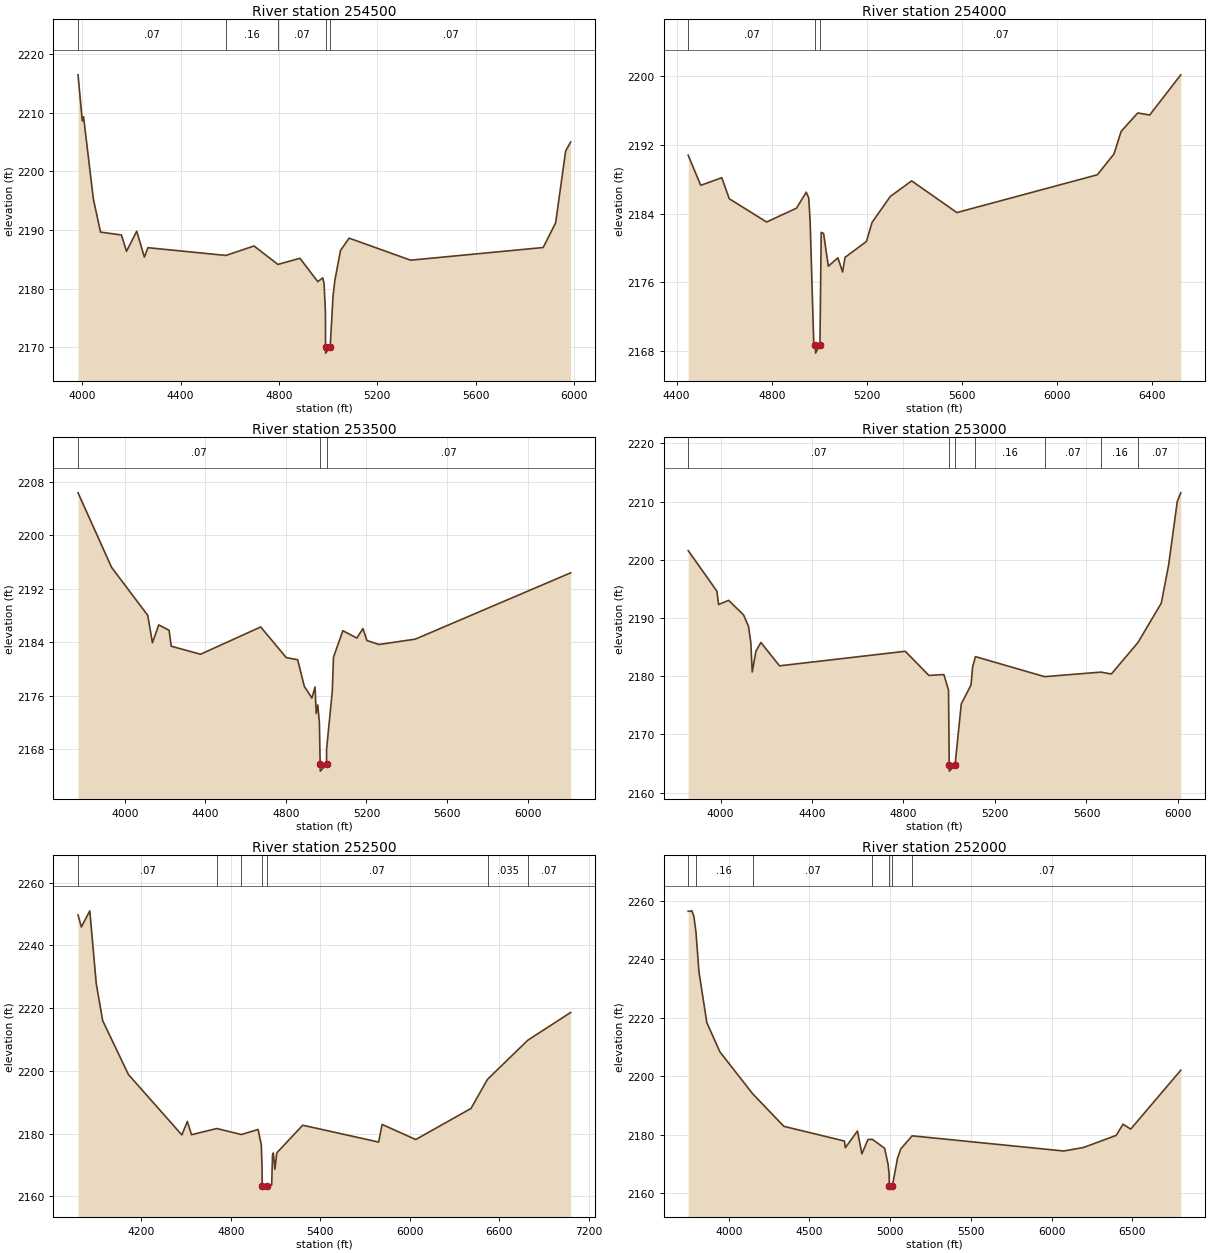
Type RM Length L Ch R = 1,254500,500,500,500
BEGIN DESCRIPTION:
Sweetwater Creek 507.0
END DESCRIPTION:
XS GIS Cut Line= 3
      1370404.98      6833787.99      1371385.21      6834057.46
      1372354.95      6834237.99
#Sta/Elev= 30
  3983.4 2216.48  4000.6 2208.63  4005.8 2209.33  4045.6 2195.34  4074.7 2189.66
  4159.7 2189.17  4180.5 2186.39  4222.0 2189.81  4253.1 2185.39  4267.5 2187.00
  4584.4 2185.68  4699.0 2187.29  4796.0 2184.15  4885.7 2185.19  4958.3 2181.21
  4978.5 2181.86  4983.7 2180.87  4989.4 2176.05  4989.7 2170.02  4990.2 2169.02
  5008.6 2170.02  5020.1 2178.68  5027.7 2181.44  5050.6 2186.52  5085.6 2188.63
  5335.5 2184.87  5874.6 2187.03  5925.4 2191.24  5966.1 2203.50  5986.4 2205.02
#Mann=5,-1,0
  3983.4    0.07       0  4584.4    0.16       0  4796.0    0.07       0
  4989.7    0.07       0  5008.6    0.07       0
Bank Sta=4989.7,5008.6
Exp/Cntr=0.3,0.1

Type RM Length L Ch R = 1,254000,500,500,500
BEGIN DESCRIPTION:
Sweetwater Creek 506.0
END DESCRIPTION:
XS GIS Cut Line= 3
      1370505.03      6834138.01      1371027.30      6834315.19
      1372545.64      6834369.06
#Sta/Elev= 30
  4448.5 2190.79  4501.3 2187.28  4589.8 2188.17  4621.2 2185.72  4778.2 2183.01
  4903.8 2184.62  4944.8 2186.48  4955.3 2185.82  4961.3 2183.05  4976.5 2168.74
  4983.5 2168.74  4984.0 2167.74  5002.4 2168.74  5007.7 2181.80  5017.7 2181.68
  5037.7 2177.86  5077.8 2178.84  5097.8 2177.19  5107.8 2178.89  5197.8 2180.74
  5221.5 2182.96  5297.9 2185.98  5387.9 2187.80  5578.1 2184.11  6168.4 2188.51
  6238.5 2190.93  6268.5 2193.56  6338.5 2195.71  6388.6 2195.47  6519.3 2200.15
#Mann=3,-1,0
  4448.5    0.07       0  4983.5    0.07       0  5002.4    0.07       0
Bank Sta=4983.5,5002.4
Exp/Cntr=0.3,0.1

Type RM Length L Ch R = 1,253500,500,500,500
BEGIN DESCRIPTION:
Sweetwater Creek 505.0
END DESCRIPTION:
XS GIS Cut Line= 6
      1370177.76      6834303.59      1371206.45      6834658.69
      1371331.00      6834587.73      1371352.82      6834499.79
      1371833.98      6834496.44      1372466.28      6834609.48
#Sta/Elev= 30
  3768.4 2206.33  3934.7 2195.20  4114.6 2188.01  4137.7 2183.92  4168.9 2186.59
  4220.4 2185.78  4231.3 2183.40  4376.6 2182.20  4675.3 2186.28  4802.2 2181.70
  4858.7 2181.38  4891.8 2177.41  4929.3 2175.65  4945.1 2177.31  4950.9 2173.35
  4958.6 2174.62  4966.7 2171.99  4970.5 2165.73  4971.3 2164.73  5002.0 2165.73
  5002.4 2168.03  5030.6 2176.62  5036.6 2181.75  5083.1 2185.72  5152.8 2184.62
  5182.8 2186.04  5202.8 2184.25  5262.8 2183.66  5442.8 2184.46  6214.1 2194.37
#Mann=3,-1,0
  3768.4    0.07       0  4970.5    0.07       0  5002.0    0.07       0
Bank Sta=4970.5,5002
Exp/Cntr=0.3,0.1

Type RM Length L Ch R = 1,253000,500,500,500
BEGIN DESCRIPTION:
Sweetwater Creek 504.0
END DESCRIPTION:
XS GIS Cut Line= 3
      1370254.99      6834438.00      1371255.49      6834987.16
      1372205.04      6835338.01
#Sta/Elev= 30
  3858.7 2201.59  3984.2 2194.62  3991.8 2192.32  4035.4 2193.04  4100.8 2190.54
  4122.6 2188.55  4132.5 2185.78  4138.7 2180.73  4154.8 2184.30  4176.6 2185.80
  4258.0 2181.79  4807.8 2184.29  4911.1 2180.14  4976.6 2180.29  4996.9 2177.61
  5000.0 2164.70  5000.6 2163.70  5025.2 2164.70  5052.8 2175.27  5095.4 2178.51
  5102.1 2181.57  5114.5 2183.37  5416.7 2179.93  5663.6 2180.71  5708.9 2180.39
  5825.0 2185.79  5927.0 2192.55  5959.0 2199.08  5997.0 2210.03  6012.3 2211.51
#Mann=7,-1,0
  3858.7    0.07       0  5000.0    0.07       0  5025.2    0.07       0
  5114.5    0.16       0  5416.7    0.07       0  5663.6    0.16       0
  5825.0    0.07       0
Bank Sta=5000,5025.2
Exp/Cntr=0.3,0.1

Type RM Length L Ch R = 1,252500,500,500,500
BEGIN DESCRIPTION:
Sweetwater Creek 503.0
END DESCRIPTION:
XS GIS Cut Line= 3
      1369904.99      6834438.00      1370908.04      6835140.88
      1372804.98      6835987.99
#Sta/Elev= 30
  3775.2 2249.74  3797.4 2245.89  3854.1 2251.05  3897.3 2227.83  3940.4 2216.01
  4113.0 2198.83  4471.2 2179.56  4507.9 2183.87  4535.8 2179.63  4705.1 2181.60
  4870.0 2179.69  4982.1 2181.30  5003.7 2176.47  5009.2 2168.51  5009.3 2163.27
  5010.1 2162.27  5040.8 2163.27  5073.3 2163.61  5078.8 2173.03  5084.3 2173.81
  5095.2 2168.61  5107.5 2173.84  5281.4 2182.66  5790.3 2177.28  5813.5 2182.91
  6038.9 2178.09  6409.5 2188.01  6520.4 2197.31  6790.0 2209.76  7077.5 2218.63
#Mann=7,-1,0
  3775.2    0.07       0  4705.1    0.16       0  4870.0    0.07       0
  5009.3    0.07       0  5040.8    0.07       0  6520.4   0.035       0
  6790.0    0.07       0
Bank Sta=5009.3,5040.8
Exp/Cntr=0.3,0.1

Type RM Length L Ch R = 1,252000,500,500,500
BEGIN DESCRIPTION:
Sweetwater Creek 502.0
END DESCRIPTION:
XS GIS Cut Line= 4
      1369905.00      6834488.00      1370422.47      6835384.78
      1370610.49      6835489.93      1372361.14      6835904.62
#Sta/Elev= 30
  3749.2 2256.49  3772.3 2256.67  3784.4 2254.83  3797.6 2249.31  3816.0 2235.73
  3864.8 2218.36  3945.5 2208.38  4148.1 2194.03  4341.6 2182.86  4716.4 2177.82
  4722.2 2175.54  4797.3 2181.26  4824.7 2173.43  4862.4 2178.34  4889.8 2178.40
  4965.2 2175.37  4986.9 2169.85  4993.7 2166.23  4994.0 2162.35  4994.5 2161.35
  5012.9 2162.35  5045.7 2172.03  5066.3 2175.20  5136.2 2179.61  6073.4 2174.41
  6196.7 2175.60  6399.4 2179.76  6441.6 2183.60  6489.0 2181.91  6799.1 2202.08
#Mann=7,-1,0
  3749.2    0.07       0  3797.6    0.16       0  4148.1    0.07       0
  4889.8    0.16       0  4994.0    0.07       0  5012.9    0.16       0
  5136.2    0.07       0
Bank Sta=4994,5012.9
Exp/Cntr=0.3,0.1