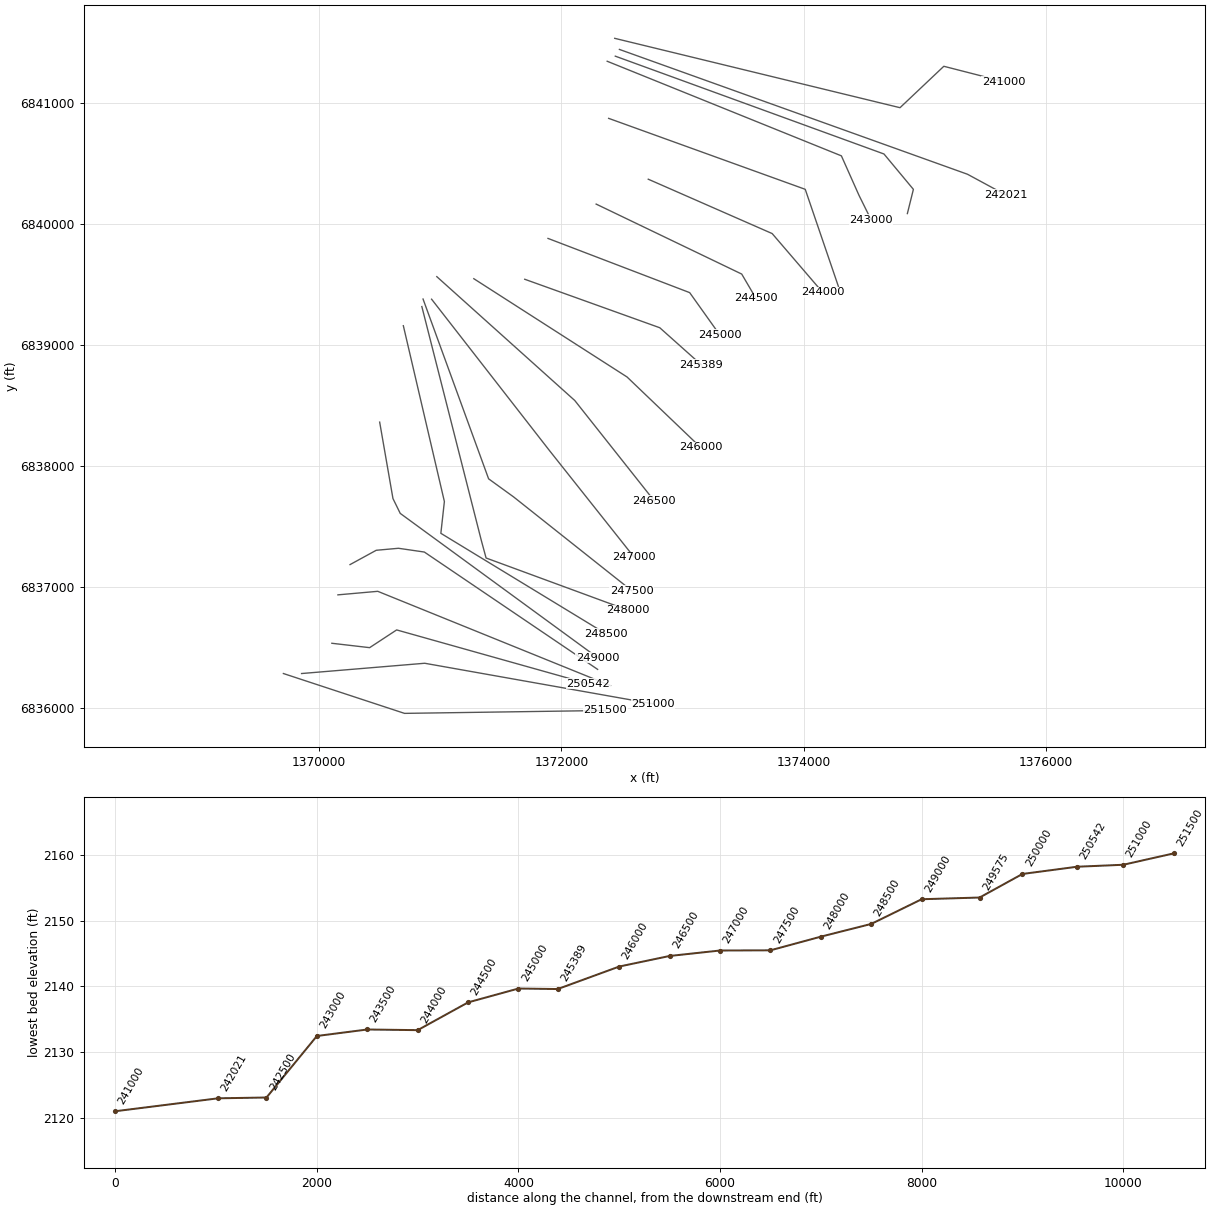
HEC-RAS study Sweetwater Creek.prj: Sweetwater Creek Base Level Engineering

--- Sweetwater Creek.g01 (geometry) --- (continued)

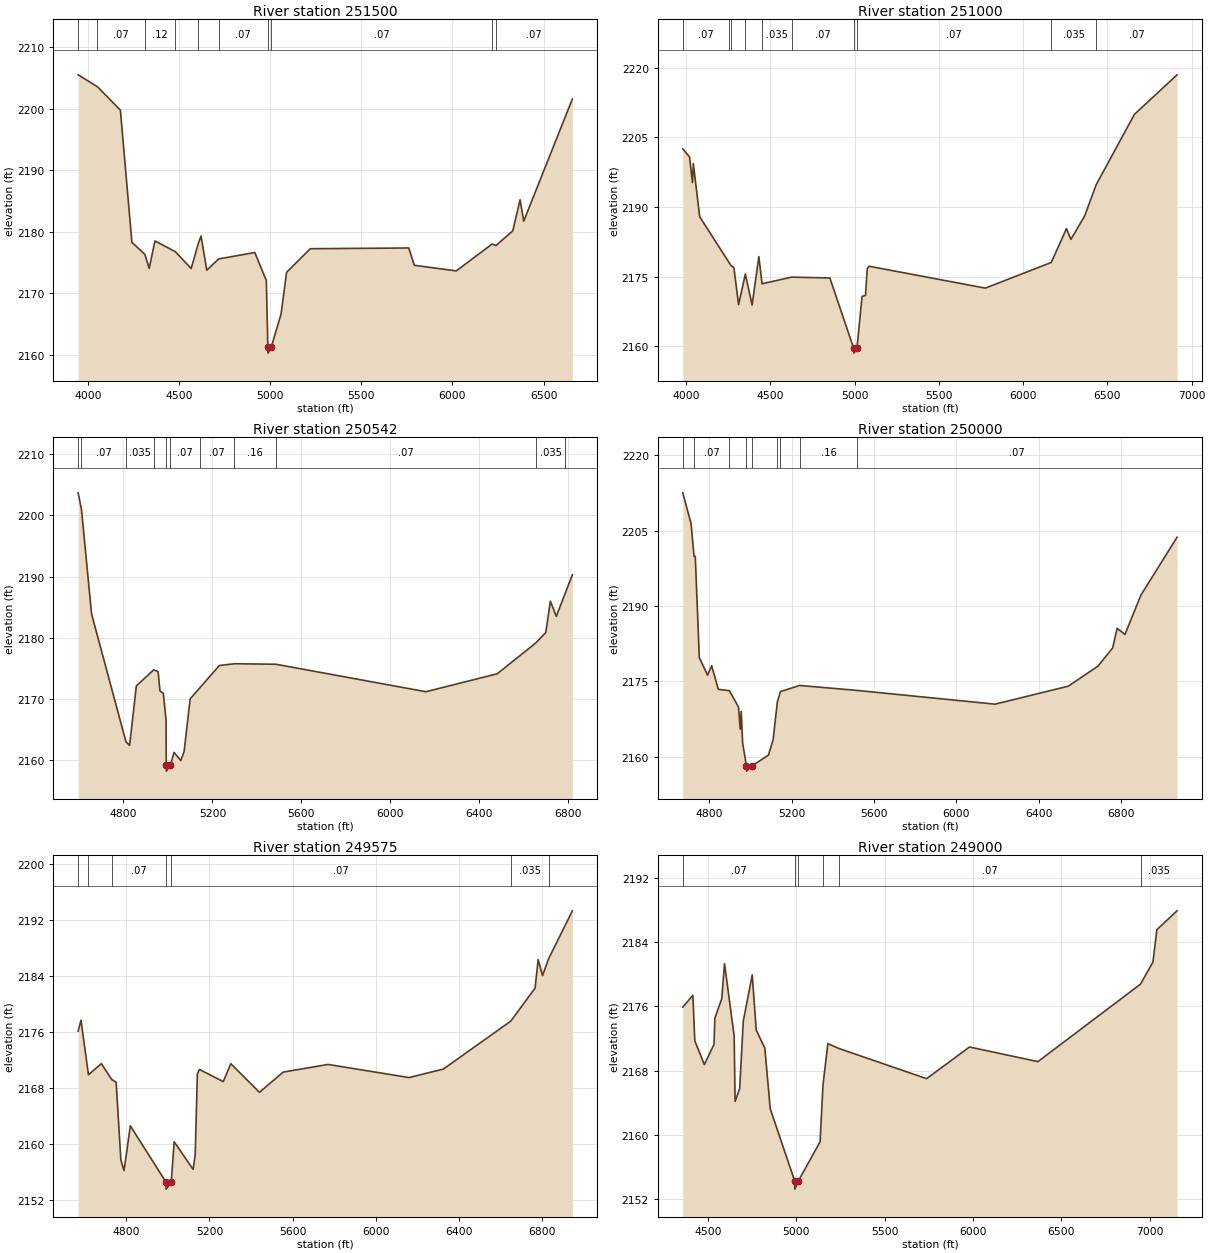
Type RM Length L Ch R = 1,251500,500,500,500
BEGIN DESCRIPTION:
Sweetwater Creek 501.0
END DESCRIPTION:
XS GIS Cut Line= 3
      1369704.96      6836288.01      1370704.55      6835958.81
      1372361.88      6835982.76
#Sta/Elev= 30
  3947.6 2205.50  4053.7 2203.56  4179.3 2199.76  4242.4 2178.27  4313.3 2176.30
  4337.2 2174.03  4368.8 2178.48  4479.9 2176.76  4567.3 2174.00  4606.8 2178.09
  4621.5 2179.29  4653.0 2173.73  4718.0 2175.56  4916.2 2176.60  4979.4 2172.06
  4987.8 2161.24  4988.3 2160.24  5006.8 2161.24  5060.5 2166.63  5090.5 2173.38
  5220.5 2177.22  5760.5 2177.34  5790.5 2174.53  6020.6 2173.61  6217.2 2177.98
  6238.9 2177.75  6330.6 2180.13  6370.6 2185.18  6390.6 2181.70  6657.5 2201.58
#Mann=10,-1,0
  3947.6   0.035       0  4053.7    0.07       0  4313.3    0.12       0
  4479.9    0.07       0  4606.8    0.16       0  4718.0    0.07       0
  4987.8    0.07       0  5006.8    0.07       0  6217.2   0.035       0
  6238.9    0.07       0
Bank Sta=4987.8,5006.8
Exp/Cntr=0.3,0.1

Type RM Length L Ch R = 1,251000,458,458,458
BEGIN DESCRIPTION:
Sweetwater Creek 500.0
END DESCRIPTION:
XS GIS Cut Line= 3
      1369854.99      6836288.00      1370871.26      6836372.85
      1372755.03      6836038.00
#Sta/Elev= 30
  3980.2 2202.49  4020.3 2200.79  4037.9 2195.24  4042.9 2199.35  4080.6 2187.89
  4252.2 2178.18  4268.4 2177.30  4283.5 2176.96  4311.4 2168.95  4351.7 2175.54
  4391.6 2168.87  4431.8 2179.30  4450.8 2173.45  4626.6 2174.88  4853.2 2174.70
  4994.7 2159.51  4995.2 2158.51  5013.7 2159.51  5044.4 2170.73  5064.7 2170.93
  5074.9 2176.72  5085.1 2177.23  5775.7 2172.51  6167.0 2178.04  6257.2 2185.33
  6283.6 2183.01  6364.8 2188.03  6433.2 2194.76  6660.3 2209.93  6913.3 2218.45
#Mann=10,-1,0
  3980.2    0.07       0  4252.2    0.12       0  4268.4   0.035       0
  4351.7    0.07       0  4450.8   0.035       0  4626.6    0.07       0
  4994.7    0.07       0  5013.7    0.07       0  6167.0   0.035       0
  6433.2    0.07       0
Bank Sta=4994.7,5013.7
Exp/Cntr=0.3,0.1

Type RM Length L Ch R = 1,250542,542,542,542
BEGIN DESCRIPTION:
Sweetwater Creek 499.0
END DESCRIPTION:
XS GIS Cut Line= 4
      1370104.99      6836538.00      1370416.64      6836501.77
      1370639.68      6836648.30      1372220.37      6836203.50
#Sta/Elev= 30
  4596.1 2203.67  4611.2 2200.94  4656.5 2183.89  4811.2 2163.00  4827.7 2162.42
  4857.9 2172.13  4935.9 2174.76  4955.8 2174.47  4964.2 2171.31  4979.3 2170.92
  4991.6 2166.48  4992.4 2159.21  4992.9 2158.21  5011.4 2159.21  5027.5 2161.28
  5057.6 2159.93  5072.7 2161.42  5099.8 2170.00  5143.9 2171.84  5231.1 2175.46
  5298.7 2175.75  5485.2 2175.67  6160.0 2171.18  6480.8 2174.11  6653.3 2179.12
  6699.0 2180.84  6719.7 2185.98  6746.3 2183.49  6787.5 2187.36  6818.8 2190.28
#Mann=11,-1,0
  4596.1   0.035       0  4611.2    0.07       0  4811.2   0.035       0
  4935.9    0.07       0  4992.4    0.07       0  5011.4    0.07       0
  5143.9    0.07       0  5298.7    0.16       0  5485.2    0.07       0
  6653.3   0.035       0  6787.5    0.07       0
Bank Sta=4992.4,5011.4
Exp/Cntr=0.3,0.1

Type RM Length L Ch R = 1,250000,425,425,425
BEGIN DESCRIPTION:
Sweetwater Creek 498.0
END DESCRIPTION:
XS GIS Cut Line= 3
      1370154.95      6836938.00      1370483.66      6836967.19
      1372404.97      6836188.01
#Sta/Elev= 30
  4670.0 2212.51  4710.2 2206.40  4725.0 2199.88  4730.9 2199.87  4750.4 2179.72
  4790.5 2176.22  4810.6 2178.11  4842.7 2173.39  4896.3 2173.13  4941.1 2169.88
  4949.4 2165.46  4954.4 2168.99  4961.2 2162.65  4979.9 2158.11  4980.5 2157.11
  5005.2 2158.11  5086.7 2160.30  5109.4 2163.38  5129.8 2170.85  5144.9 2172.94
  5237.9 2174.16  5519.4 2173.17  6188.5 2170.44  6544.6 2174.02  6688.9 2178.01
  6760.4 2181.64  6782.0 2185.54  6820.1 2184.32  6897.8 2192.15  7073.3 2203.66
#Mann=9,-1,0
  4670.0   0.035       0  4725.0    0.07       0  4896.3   0.035       0
  4979.9   0.035       0  5005.2   0.035       0  5129.8    0.07       0
  5144.9   0.035       0  5237.9    0.16       0  5519.4    0.07       0
Bank Sta=4979.9,5005.2
Exp/Cntr=0.3,0.1

Type RM Length L Ch R = 1,249575,575,575,575
BEGIN DESCRIPTION:
Sweetwater Creek 497.0
END DESCRIPTION:
XS GIS Cut Line= 5
      1370254.98      6837187.99      1370471.04      6837306.21
      1370654.50      6837322.80      1370868.31      6837291.65
      1372298.40      6836322.34
#Sta/Elev= 30
  4569.5 2176.13  4583.3 2177.71  4619.1 2169.89  4681.0 2171.49  4730.2 2169.24
  4752.1 2168.81  4774.7 2157.71  4790.0 2156.18  4820.3 2162.58  4991.6 2154.52
  4992.2 2153.52  5016.9 2154.52  5030.8 2160.29  5121.8 2156.35  5131.9 2158.43
  5142.2 2170.02  5152.1 2170.65  5266.8 2168.91  5302.7 2171.48  5440.5 2167.38
  5554.3 2170.27  5770.0 2171.37  6159.3 2169.49  6324.1 2170.71  6647.7 2177.57
  6764.4 2182.29  6779.3 2186.38  6800.3 2184.09  6829.3 2186.49  6943.7 2193.36
#Mann=7,-1,0
  4569.5    0.07       0  4619.1   0.035       0  4730.2    0.07       0
  4991.6    0.07       0  5016.9    0.07       0  6647.7   0.035       0
  6829.3    0.07       0
Bank Sta=4991.6,5016.9
Exp/Cntr=0.3,0.1

Type RM Length L Ch R = 1,249000,500,500,500
BEGIN DESCRIPTION:
Sweetwater Creek 496.0
END DESCRIPTION:
XS GIS Cut Line= 4
      1370499.50      6838365.14      1370609.19      6837733.70
      1370669.28      6837610.95      1372296.85      6836420.39
#Sta/Elev= 30
  4359.1 2175.91  4416.2 2177.38  4427.2 2171.72  4481.0 2168.76  4535.6 2171.27
  4540.6 2174.54  4579.5 2176.96  4595.2 2181.32  4649.8 2172.31  4654.9 2164.17
  4681.0 2165.80  4701.3 2174.18  4752.0 2179.93  4774.2 2173.06  4823.1 2170.80
  4853.5 2163.27  4991.9 2154.26  4992.4 2153.26  5012.2 2154.26  5135.5 2159.16
  5151.7 2166.20  5179.4 2171.37  5240.0 2170.78  5737.6 2167.01  5980.1 2170.95
  6366.9 2169.13  6947.0 2178.78  7017.0 2181.53  7039.4 2185.56  7153.2 2187.90
#Mann=6,-1,0
  4359.1    0.07       0  4991.9    0.07       0  5012.2    0.07       0
  5151.7    0.16       0  5240.0    0.07       0  6947.0   0.035       0
Bank Sta=4991.9,5012.2
Exp/Cntr=0.3,0.1

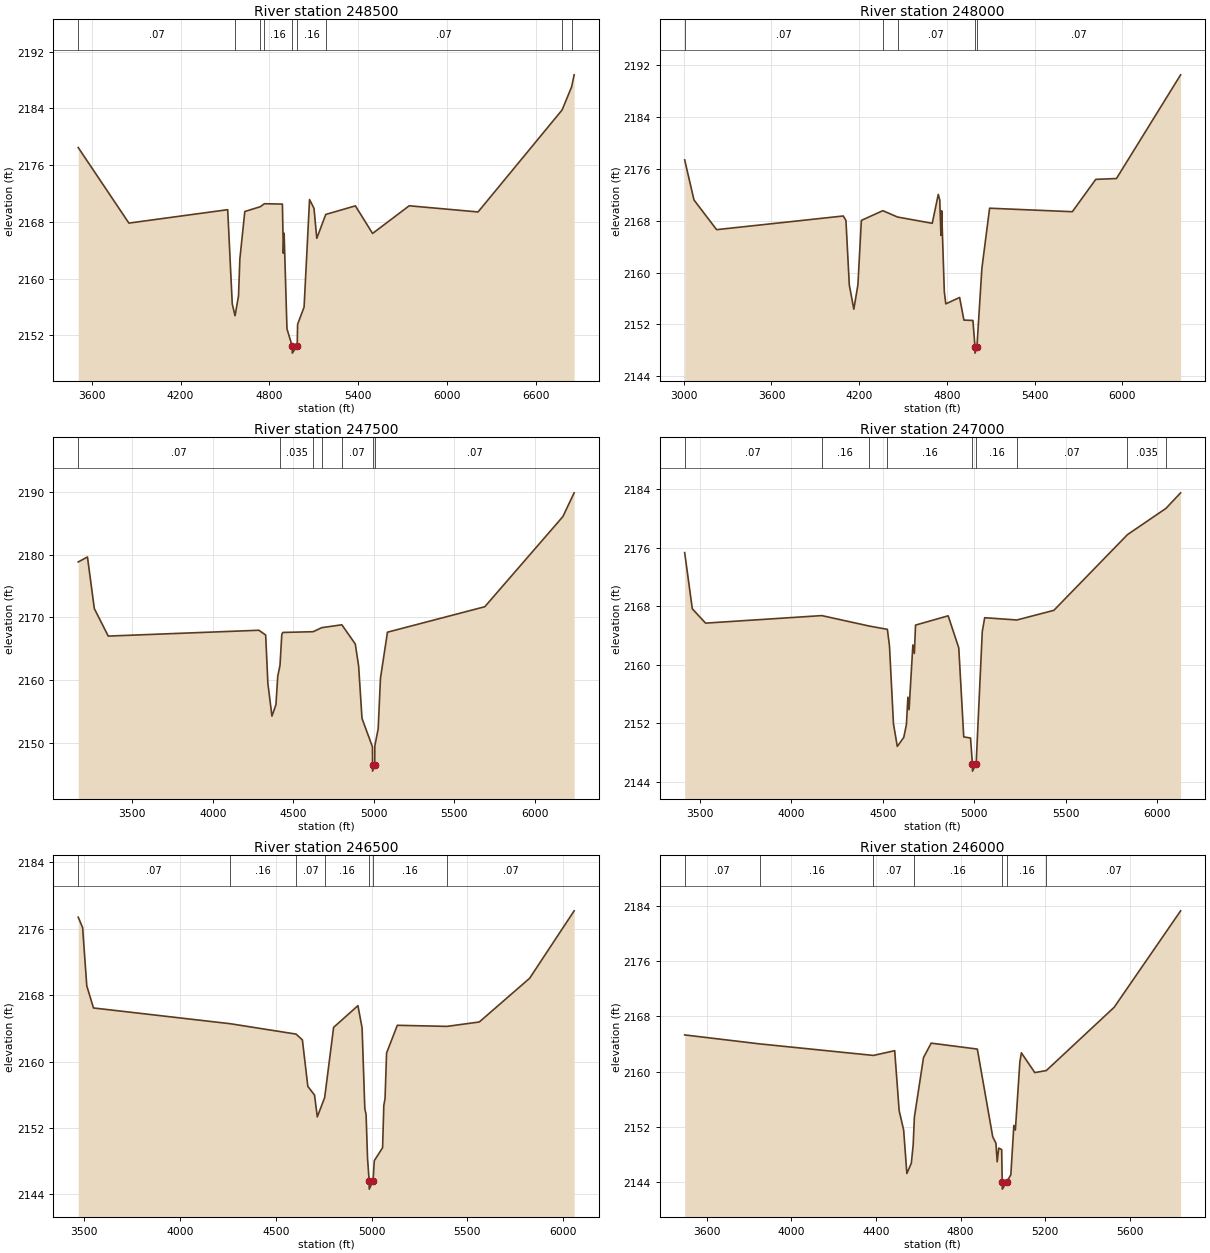
Type RM Length L Ch R = 1,248500,500,500,500
BEGIN DESCRIPTION:
Sweetwater Creek 495.0
END DESCRIPTION:
XS GIS Cut Line= 4
      1370694.85      6839161.56      1371033.64      6837709.15
      1371004.54      6837446.40      1372366.56      6836616.50
#Sta/Elev= 30
  3508.6 2178.48  3851.1 2167.83  4518.6 2169.72  4549.4 2156.43  4568.3 2154.77
  4591.7 2157.57  4600.7 2162.77  4634.2 2169.46  4739.0 2170.14  4766.6 2170.56
  4888.2 2170.51  4894.6 2163.57  4899.8 2166.40  4919.0 2152.93  4954.3 2150.50
  4955.0 2149.50  4988.1 2150.50  4990.9 2153.56  5034.7 2155.99  5071.6 2171.15
  5101.8 2169.90  5120.4 2165.68  5181.1 2169.05  5381.2 2170.26  5497.4 2166.37
  5745.0 2170.27  6210.1 2169.40  6778.3 2183.79  6842.2 2187.04  6859.3 2188.73
#Mann=9,-1,0
  3508.6    0.07       0  4568.3    0.16       0  4739.0    0.07       0
  4766.6    0.16       0  4954.3    0.07       0  4988.1    0.16       0
  5181.1    0.07       0  6778.3   0.035       0  6842.2    0.07       0
Bank Sta=4954.3,4988.1
Exp/Cntr=0.3,0.1

Type RM Length L Ch R = 1,248000,500,500,500
BEGIN DESCRIPTION:
Sweetwater Creek 494.0
END DESCRIPTION:
XS GIS Cut Line= 4
      1370847.58      6839319.80      1371338.53      6837387.49
      1371377.75      6837242.49      1372550.36      6836810.68
#Sta/Elev= 30
  3006.3 2177.37  3070.1 2171.19  3224.8 2166.61  4091.5 2168.72  4109.8 2168.03
  4132.8 2158.07  4163.7 2154.34  4191.7 2158.10  4215.3 2168.04  4362.3 2169.54
  4462.6 2168.56  4700.3 2167.59  4741.5 2172.05  4751.8 2171.19  4759.7 2165.74
  4764.8 2169.52  4782.8 2157.06  4793.1 2155.16  4887.6 2156.15  4916.9 2152.66
  4978.8 2152.60  4992.7 2148.56  4993.0 2147.56  5006.2 2148.56  5039.8 2160.60
  5092.7 2169.92  5658.8 2169.38  5819.1 2174.37  5960.8 2174.50  6399.8 2190.50
#Mann=5,-1,0
  3006.3    0.07       0  4362.3   0.035       0  4462.6    0.07       0
  4992.7    0.07       0  5006.2    0.07       0
Bank Sta=4992.7,5006.2
Exp/Cntr=0.3,0.1

Type RM Length L Ch R = 1,247500,500,500,500
BEGIN DESCRIPTION:
Sweetwater Creek 493.0
END DESCRIPTION:
XS GIS Cut Line= 4
      1370857.53      6839381.97      1371398.62      6837896.65
      1371604.85      6837747.20      1372579.46      6836972.98
#Sta/Elev= 30
  3164.5 2178.81  3221.9 2179.61  3264.6 2171.38  3351.0 2167.00  4286.7 2167.93
  4328.8 2167.17  4342.5 2159.46  4367.8 2154.25  4392.7 2156.09  4403.7 2160.58
  4417.8 2162.34  4428.9 2167.26  4435.2 2167.58  4624.2 2167.70  4676.4 2168.34
  4801.9 2168.80  4885.4 2165.74  4906.2 2162.21  4927.1 2153.88  4992.1 2149.35
  4992.6 2146.48  4992.9 2145.48  5006.2 2146.48  5006.7 2149.49  5027.5 2152.22
  5041.9 2160.31  5085.2 2167.62  5689.8 2171.68  6174.6 2186.04  6244.7 2189.83
#Mann=7,-1,0
  3164.5    0.07       0  4417.8   0.035       0  4624.2    0.07       0
  4676.4   0.035       0  4801.9    0.07       0  4992.6    0.07       0
  5006.2    0.07       0
Bank Sta=4992.6,5006.2
Exp/Cntr=0.3,0.1

Type RM Length L Ch R = 1,247000,500,500,500
BEGIN DESCRIPTION:
Sweetwater Creek 492.0
END DESCRIPTION:
XS GIS Cut Line= 3
      1370928.03      6839380.64      1371899.21      6838132.34
      1372599.26      6837249.64
#Sta/Elev= 30
  3418.4 2175.33  3460.1 2167.65  3532.5 2165.69  4167.1 2166.72  4424.6 2165.30
  4525.3 2164.84  4536.7 2162.60  4558.6 2151.91  4579.5 2148.83  4614.7 2150.06
  4629.2 2151.81  4637.4 2155.57  4643.7 2153.85  4664.5 2162.71  4672.7 2161.54
  4679.0 2165.42  4857.3 2166.69  4915.2 2162.30  4942.3 2150.13  4979.4 2149.98
  4989.7 2146.45  4990.2 2145.45  5010.1 2146.45  5043.5 2164.52  5056.6 2166.43
  5232.6 2166.12  5434.4 2167.44  5836.2 2177.79  6046.4 2181.38  6126.6 2183.51
#Mann=9,-1,0
  3418.4    0.07       0  4167.1    0.16       0  4424.6    0.07       0
  4525.3    0.16       0  4989.7    0.07       0  5010.1    0.16       0
  5232.6    0.07       0  5836.2   0.035       0  6046.4    0.07       0
Bank Sta=4989.7,5010.1
Exp/Cntr=0.3,0.1

Type RM Length L Ch R = 1,246500,500,500,500
BEGIN DESCRIPTION:
Sweetwater Creek 491.0
END DESCRIPTION:
XS GIS Cut Line= 3
      1370971.14      6839566.83      1372110.06      6838543.39
      1372766.58      6837713.72
#Sta/Elev= 30
  3468.8 2177.40  3491.8 2176.16  3513.5 2169.13  3548.6 2166.46  4262.8 2164.56
  4606.2 2163.31  4639.2 2162.61  4667.6 2157.01  4702.7 2155.95  4717.0 2153.33
  4755.5 2155.66  4802.2 2164.12  4929.2 2166.74  4950.9 2164.05  4965.1 2154.33
  4971.8 2153.60  4979.3 2148.35  4987.8 2145.62  4988.2 2144.62  5008.1 2145.62
  5014.6 2148.05  5057.9 2149.61  5064.3 2154.72  5070.7 2155.52  5078.7 2161.03
  5134.8 2164.37  5394.5 2164.24  5562.8 2164.77  5825.6 2170.04  6058.0 2178.17
#Mann=7,-1,0
  3468.8    0.07       0  4262.8    0.16       0  4606.2    0.07       0
  4755.5    0.16       0  4987.8    0.07       0  5008.1    0.16       0
  5394.5    0.07       0
Bank Sta=4987.8,5008.1
Exp/Cntr=0.3,0.1

Type RM Length L Ch R = 1,246000,611,611,611
BEGIN DESCRIPTION:
Sweetwater Creek 490.0
END DESCRIPTION:
XS GIS Cut Line= 3
      1371276.60      6839549.92      1372541.45      6838737.84
      1373147.80      6838156.95
#Sta/Elev= 30
  3496.9 2165.33  3851.7 2164.03  4388.6 2162.36  4489.0 2163.05  4510.1 2154.37
  4531.3 2151.56  4546.5 2145.27  4567.6 2146.77  4576.4 2149.44  4582.0 2153.41
  4625.1 2162.05  4661.4 2164.14  4879.4 2163.28  4952.1 2150.59  4967.3 2149.65
  4973.2 2146.97  4980.5 2148.95  4994.4 2148.74  4996.9 2144.01  4997.4 2143.01
  5017.3 2144.01  5037.7 2145.09  5051.9 2152.23  5059.1 2151.56  5080.2 2161.38
  5087.4 2162.74  5150.9 2159.88  5205.2 2160.17  5525.8 2169.33  5839.7 2183.29
#Mann=7,-1,0
  3496.9    0.07       0  3851.7    0.16       0  4388.6    0.07       0
  4582.0    0.16       0  4996.9    0.07       0  5017.3    0.16       0
  5205.2    0.07       0
Bank Sta=4996.9,5017.3
Exp/Cntr=0.3,0.1

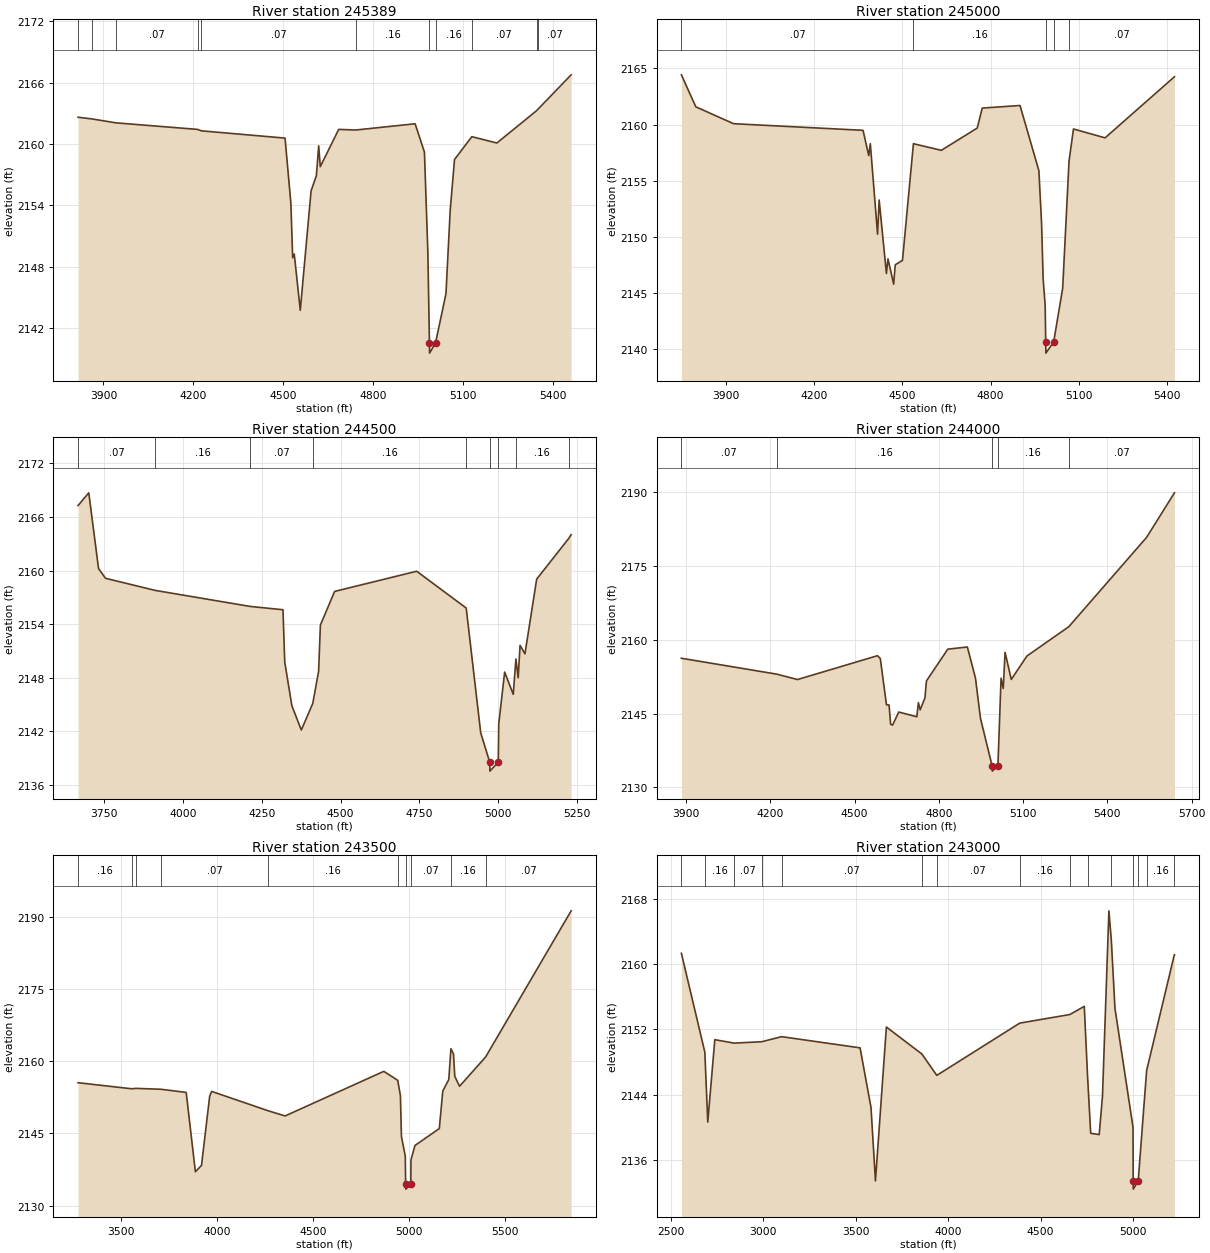
Type RM Length L Ch R = 1,245389,389,389,389
BEGIN DESCRIPTION:
Sweetwater Creek 489.0
END DESCRIPTION:
XS GIS Cut Line= 3
      1371696.89      6839545.32      1372811.49      6839144.74
      1373154.98      6838838.02
#Sta/Elev= 30
  3815.6 2162.62  3862.7 2162.45  3941.9 2162.07  4214.2 2161.43  4227.0 2161.29
  4506.1 2160.58  4525.5 2154.23  4531.5 2148.89  4536.8 2149.26  4556.9 2143.76
  4592.9 2155.42  4610.6 2156.92  4618.3 2159.83  4623.6 2157.79  4685.1 2161.43
  4742.0 2161.37  4940.0 2161.98  4971.1 2159.21  4982.5 2149.42  4987.8 2140.58
  4988.2 2139.58  5008.1 2140.58  5042.9 2145.38  5057.1 2153.55  5071.4 2158.49
  5129.3 2160.72  5212.7 2160.10  5345.7 2163.27  5349.1 2163.38  5460.5 2166.76
#Mann=11,-1,0
  3815.6    0.07       0  3862.7    0.16       0  3941.9    0.07       0
  4214.2    0.16       0  4227.0    0.07       0  4742.0    0.16       0
  4987.8    0.07       0  5008.1    0.16       0  5129.3    0.07       0
  5345.7    0.16       0  5349.1    0.07       0
Bank Sta=4987.8,5008.1
Exp/Cntr=0.3,0.1

Type RM Length L Ch R = 1,245000,500,500,500
BEGIN DESCRIPTION:
Sweetwater Creek 488.0
END DESCRIPTION:
XS GIS Cut Line= 3
      1371889.04      6839882.68      1373058.31      6839434.83
      1373304.99      6839088.01
#Sta/Elev= 30
  3747.9 2164.43  3797.1 2161.58  3925.6 2160.08  4366.0 2159.49  4385.4 2157.24
  4390.7 2158.30  4415.4 2150.25  4420.8 2153.29  4445.5 2146.75  4450.8 2148.05
  4470.2 2145.80  4475.5 2147.52  4500.2 2147.92  4537.4 2158.30  4632.4 2157.71
  4754.5 2159.69  4771.6 2161.47  4900.1 2161.70  4964.3 2155.90  4973.4 2151.23
  4978.8 2146.27  4985.7 2143.88  4987.5 2140.66  4988.1 2139.66  5014.6 2140.66
  5045.2 2145.42  5066.9 2156.76  5082.0 2159.61  5189.5 2158.82  5425.6 2164.26
#Mann=5,-1,0
  3747.9    0.07       0  4537.4    0.16       0  4987.5    0.07       0
  5014.6    0.16       0  5066.9    0.07       0
Bank Sta=4987.5,5014.6
Exp/Cntr=0.3,0.1

Type RM Length L Ch R = 1,244500,500,500,500
BEGIN DESCRIPTION:
Sweetwater Creek 487.0
END DESCRIPTION:
XS GIS Cut Line= 3
      1372286.40      6840166.29      1373487.76      6839588.22
      1373604.99      6839388.02
#Sta/Elev= 30
  3666.8 2167.29  3700.8 2168.71  3731.8 2160.23  3754.0 2159.14  3911.0 2157.79
  4213.1 2155.99  4317.3 2155.62  4322.8 2149.77  4345.5 2144.87  4375.5 2142.15
  4411.8 2145.13  4430.4 2148.72  4436.0 2153.90  4481.2 2157.67  4741.7 2159.93
  4898.9 2155.81  4944.9 2141.85  4973.5 2138.55  4974.1 2137.55  5000.6 2138.55
  5002.2 2142.85  5020.9 2148.64  5048.2 2146.15  5056.7 2150.11  5063.9 2148.00
  5069.8 2151.63  5085.4 2150.68  5122.6 2159.05  5224.1 2163.59  5232.0 2164.03
#Mann=9,-1,0
  3666.8    0.07       0  3911.0    0.16       0  4213.1    0.07       0
  4411.8    0.16       0  4898.9    0.07       0  4973.5    0.07       0
  5000.6    0.07       0  5056.7    0.16       0  5224.1    0.07       0
Bank Sta=4973.5,5000.6
Exp/Cntr=0.3,0.1

Type RM Length L Ch R = 1,244000,500,500,500
BEGIN DESCRIPTION:
Sweetwater Creek 486.0
END DESCRIPTION:
XS GIS Cut Line= 3
      1372716.44      6840371.90      1373739.09      6839922.84
      1374155.01      6839437.99
#Sta/Elev= 30
  3883.1 2156.28  4222.2 2153.05  4296.5 2151.95  4581.4 2156.80  4591.4 2156.22
  4613.3 2146.82  4622.6 2146.77  4628.1 2142.86  4635.1 2142.68  4657.0 2145.34
  4721.5 2144.38  4727.0 2147.25  4733.4 2145.78  4750.3 2148.22  4755.8 2151.68
  4831.7 2158.13  4901.4 2158.57  4930.2 2152.26  4948.1 2144.05  4989.8 2134.32
  4990.2 2133.32  5010.1 2134.32  5021.4 2152.22  5029.1 2150.14  5035.7 2157.49
  5057.7 2151.97  5113.6 2156.74  5262.6 2162.70  5539.5 2180.86  5638.8 2189.93
#Mann=5,-1,0
  3883.1    0.07       0  4222.2    0.16       0  4989.8    0.07       0
  5010.1    0.16       0  5262.6    0.07       0
Bank Sta=4989.8,5010.1
Exp/Cntr=0.3,0.1

Type RM Length L Ch R = 1,243500,500,500,500
BEGIN DESCRIPTION:
Sweetwater Creek 485.0
END DESCRIPTION:
XS GIS Cut Line= 3
      1372389.52      6840874.61      1374012.06      6840288.37
      1374285.43      6839487.12
#Sta/Elev= 30
  3274.8 2155.53  3554.0 2154.27  3577.3 2154.35  3706.6 2154.17  3838.8 2153.51
  3886.7 2137.03  3918.6 2138.35  3961.4 2152.76  3971.8 2153.72  4265.5 2149.71
  4354.5 2148.62  4869.4 2157.89  4942.0 2156.03  4956.1 2152.85  4961.4 2144.37
  4981.5 2140.28  4983.4 2134.42  4984.0 2133.42  5010.6 2134.42  5011.0 2139.48
  5032.1 2142.49  5158.9 2146.00  5177.1 2153.79  5208.4 2156.19  5219.5 2162.58
  5232.8 2161.50  5239.7 2156.86  5264.5 2154.79  5400.6 2160.88  5846.6 2191.24
#Mann=10,-1,0
  3274.8    0.16       0  3554.0    0.07       0  3577.3    0.16       0
  3706.6    0.07       0  4265.5    0.16       0  4942.0    0.07       0
  4983.4    0.07       0  5010.6    0.07       0  5219.5    0.16       0
  5400.6    0.07       0
Bank Sta=4983.4,5010.6
Exp/Cntr=0.3,0.1

Type RM Length L Ch R = 1,243000,500,500,500
BEGIN DESCRIPTION:
Sweetwater Creek 484.0
END DESCRIPTION:
XS GIS Cut Line= 4
      1372377.44      6841346.40      1374310.46      6840564.84
      1374455.72      6840238.78      1374555.01      6840037.98
#Sta/Elev= 30
  2558.0 2161.31  2684.7 2149.21  2700.7 2140.64  2738.7 2150.73  2843.4 2150.31
  2992.4 2150.48  3100.0 2151.10  3524.1 2149.73  3583.2 2142.44  3607.3 2133.44
  3666.4 2152.28  3858.6 2148.97  3939.0 2146.36  4387.5 2152.76  4658.2 2153.81
  4736.4 2154.81  4753.8 2146.42  4771.0 2139.27  4817.1 2139.11  4834.8 2143.80
  4869.5 2166.51  4882.5 2162.96  4902.3 2154.57  5000.0 2139.98  5000.8 2133.43
  5001.4 2132.43  5028.0 2133.43  5073.5 2146.95  5223.3 2161.13  5224.0 2161.13
#Mann=15,-1,0
  2558.0    0.07       0  2684.7    0.16       0  2843.4    0.07       0
  2992.4    0.16       0  3100.0    0.07       0  3858.6    0.16       0
  3939.0    0.07       0  4387.5    0.16       0  4658.2    0.07       0
  4753.8    0.16       0  4882.5    0.07       0  5000.8    0.07       0
  5028.0    0.07       0  5073.5    0.16       0  5223.3    0.07       0
Bank Sta=5000.8,5028
Exp/Cntr=0.3,0.1

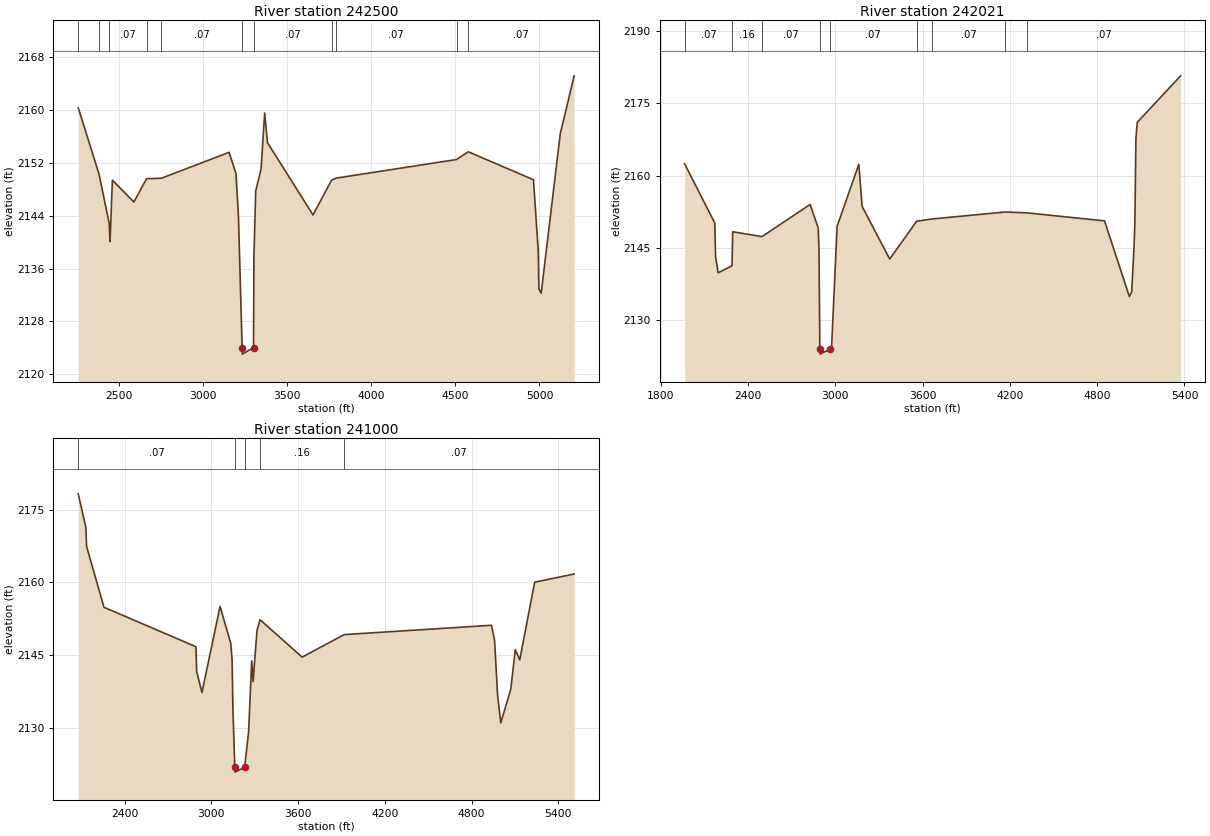
Type RM Length L Ch R = 1,242500,479,479,479
BEGIN DESCRIPTION:
Sweetwater Creek 483.0
END DESCRIPTION:
XS GIS Cut Line= 4
      1372444.30      6841388.47      1374662.01      6840580.20
      1374904.71      6840288.08      1374854.99      6840087.96
#Sta/Elev= 30
  2259.8 2160.33  2383.1 2150.34  2443.6 2142.89  2448.9 2140.10  2462.8 2149.38
  2590.5 2146.07  2666.0 2149.60  2754.1 2149.67  3155.9 2153.58  3197.2 2150.38
  3211.7 2143.93  3233.6 2124.06  3235.1 2123.06  3301.5 2124.06  3303.6 2137.60
  3314.3 2147.73  3346.2 2151.05  3367.5 2159.54  3384.5 2155.04  3654.8 2144.11
  3764.9 2149.37  3791.2 2149.68  4507.6 2152.50  4577.1 2153.67  4964.5 2149.44
  4993.1 2138.61  4996.8 2132.88  5010.4 2132.28  5123.7 2156.40  5206.2 2165.16
#Mann=11,-1,0
  2259.8    0.07       0  2383.1    0.16       0  2443.6    0.07       0
  2666.0    0.16       0  2754.1    0.07       0  3233.6    0.07       0
  3301.5    0.07       0  3764.9    0.16       0  3791.2    0.07       0
  4507.6    0.16       0  4577.1    0.07       0
Bank Sta=3233.6,3301.5
Exp/Cntr=0.3,0.1

Type RM Length L Ch R = 1,242021,1021,1021,1021
BEGIN DESCRIPTION:
Sweetwater Creek 482.0
END DESCRIPTION:
XS GIS Cut Line= 3
      1372478.32      6841444.13      1375351.16      6840412.90
      1375665.40      6840242.89
#Sta/Elev= 30
  1963.9 2162.44  2171.0 2150.14  2176.3 2143.18  2194.1 2139.82  2289.3 2141.29
  2293.9 2148.35  2495.4 2147.34  2826.0 2154.01  2882.1 2149.15  2887.4 2144.47
  2893.2 2123.94  2894.7 2122.94  2961.2 2123.94  2974.3 2124.70  3012.2 2149.50
  3161.0 2162.35  3184.2 2153.59  3373.5 2142.68  3558.6 2150.53  3667.0 2151.01
  4169.2 2152.45  4317.3 2152.27  4850.3 2150.61  5021.2 2134.89  5037.3 2135.86
  5053.5 2145.42  5059.2 2150.20  5066.1 2167.68  5075.4 2171.06  5373.5 2180.72
#Mann=9,-1,0
  1963.9    0.07       0  2289.3    0.16       0  2495.4    0.07       0
  2893.2    0.07       0  2961.2    0.07       0  3558.6    0.16       0
  3667.0    0.07       0  4169.2    0.16       0  4317.3    0.07       0
Bank Sta=2893.2,2961.2
Exp/Cntr=0.3,0.1

Type RM Length L Ch R = 1,241000,428,428,428
BEGIN DESCRIPTION:
Sweetwater Creek 480.0
END DESCRIPTION:
XS GIS Cut Line= 4
      1372439.61      6841535.75      1374794.33      6840962.74
      1375155.89      6841304.85      1375649.59      6841178.17
#Sta/Elev= 30
  2078.8 2178.24  2131.7 2171.37  2136.8 2167.42  2256.9 2154.90  2893.1 2146.78
  2898.3 2141.66  2934.9 2137.35  3060.1 2155.07  3134.1 2147.48  3143.5 2143.99
  3148.7 2134.45  3161.9 2121.97  3163.4 2120.97  3229.9 2121.97  3257.6 2129.23
  3279.0 2143.86  3288.5 2139.59  3315.6 2150.11  3336.7 2152.33  3628.1 2144.63
  3918.3 2149.27  4938.0 2151.19  4959.0 2148.12  4980.4 2136.70  5002.1 2131.10
  5071.4 2138.05  5102.3 2146.18  5133.3 2144.05  5236.5 2160.05  5509.7 2161.74
#Mann=5,-1,0
  2078.8    0.07       0  3161.9    0.07       0  3229.9    0.07       0
  3336.7    0.16       0  3918.3    0.07       0
Bank Sta=3161.9,3229.9
Exp/Cntr=0.3,0.1