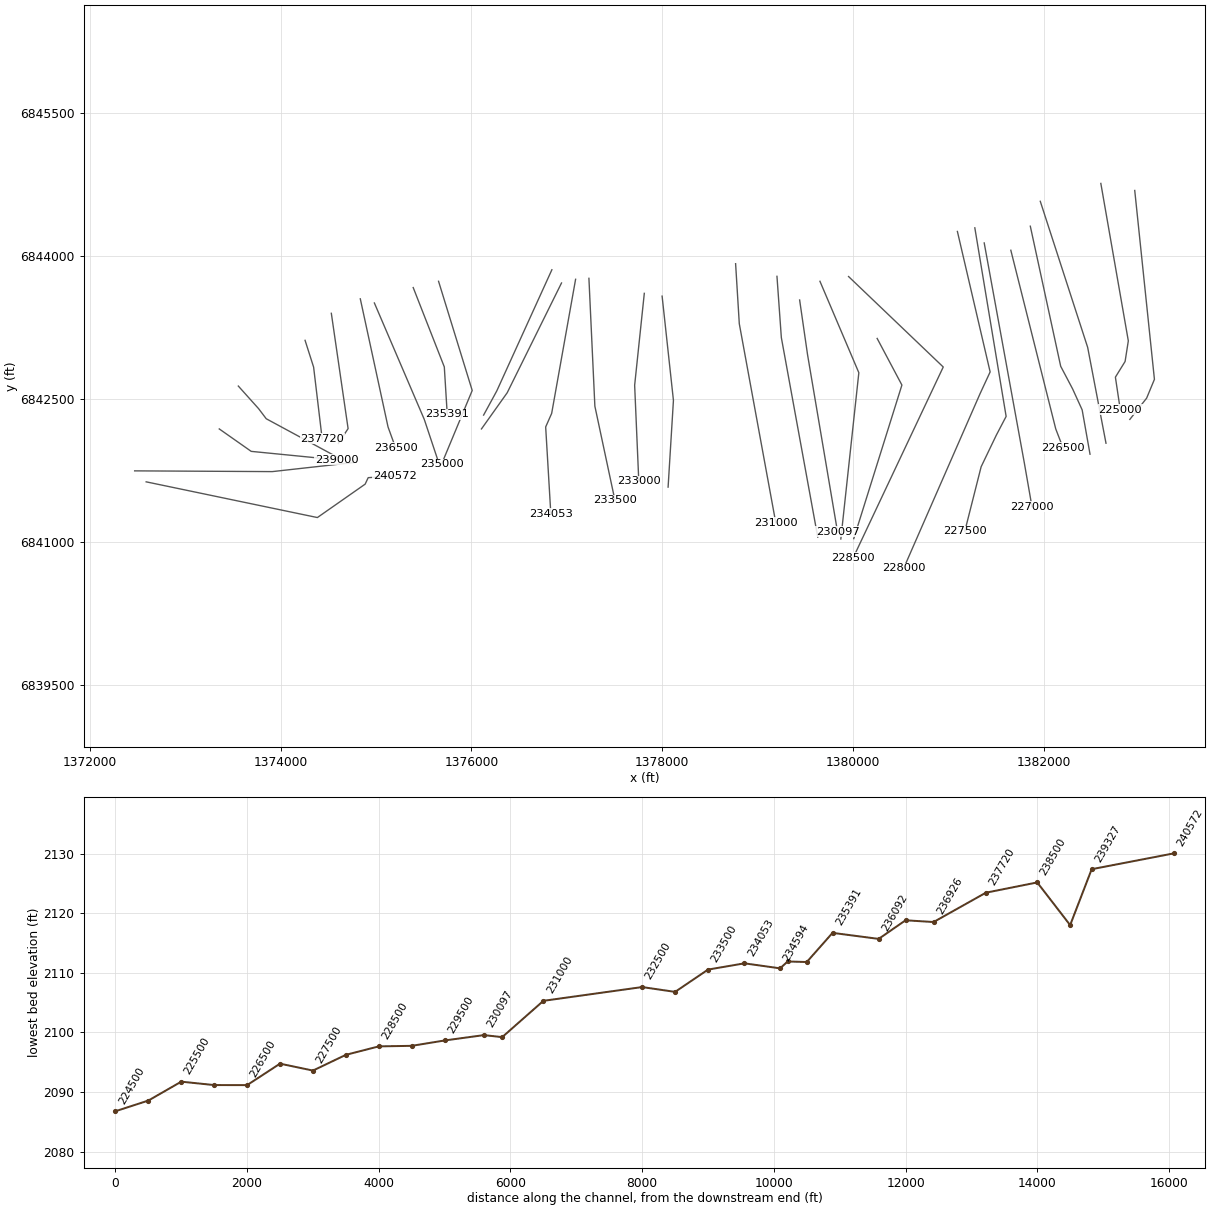
HEC-RAS study Sweetwater Creek.prj: Sweetwater Creek Base Level Engineering

--- Sweetwater Creek.g01 (geometry) --- (continued)

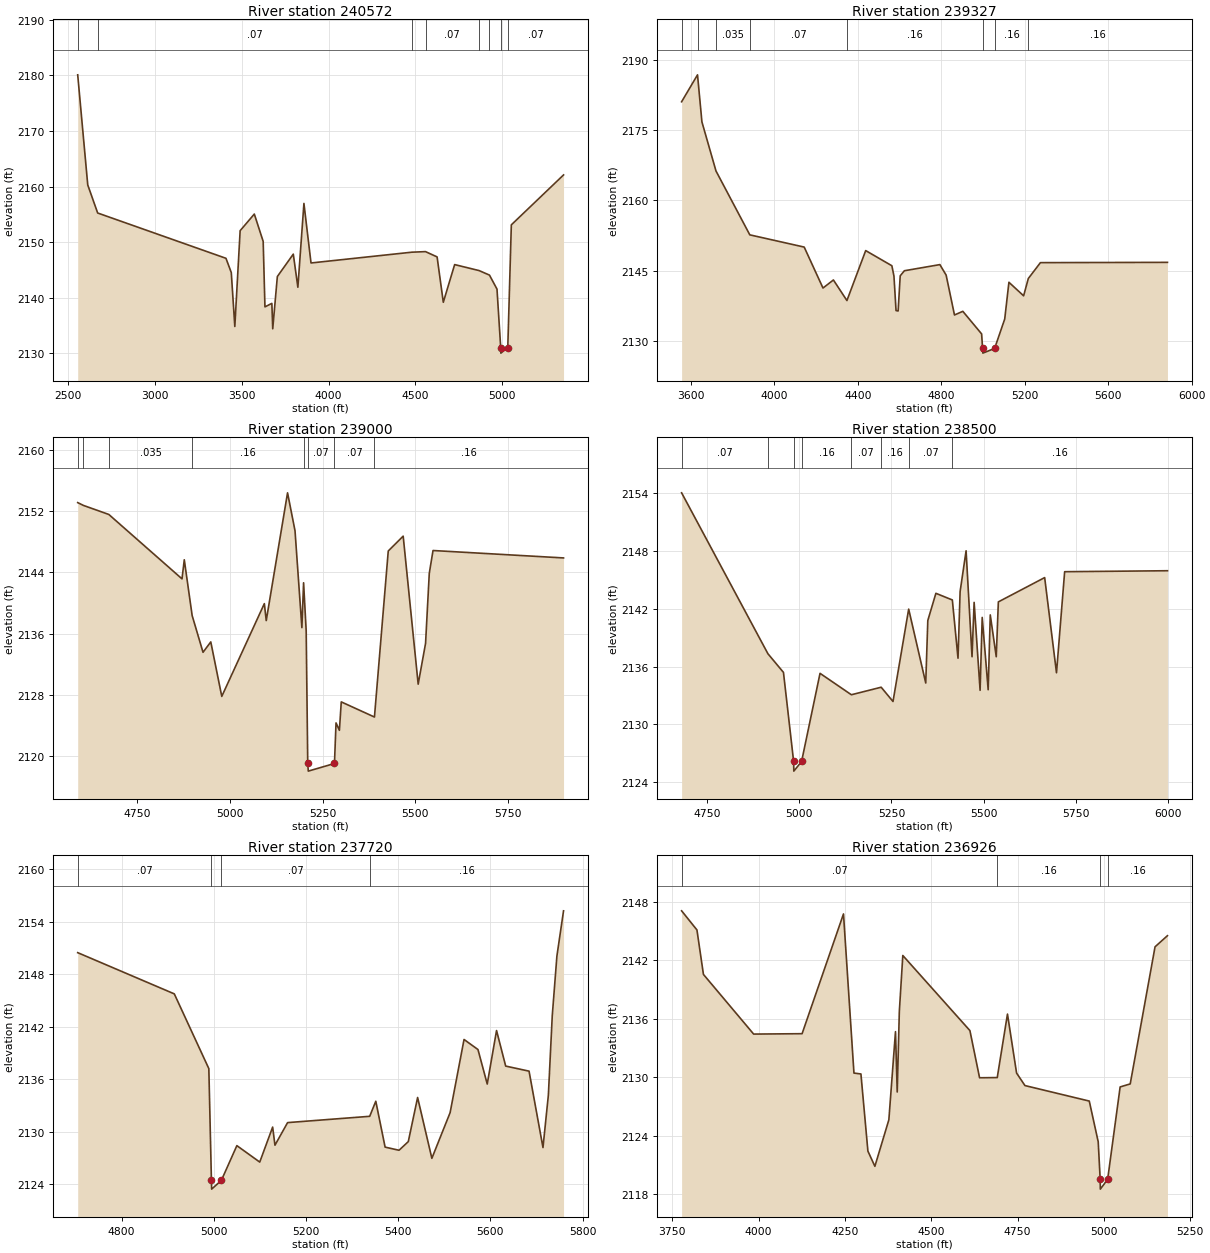
Type RM Length L Ch R = 1,240572,1245,1245,1245
BEGIN DESCRIPTION:
Sweetwater Creek 478.0
END DESCRIPTION:
XS GIS Cut Line= 5
      1372588.31      6841632.57      1374384.02      6841257.67
      1374885.19      6841608.51      1374917.00      6841676.42
      1375196.32      6841692.95
#Sta/Elev= 30
  2553.8 2180.10  2611.7 2160.29  2668.9 2155.24  3408.5 2147.09  3439.2 2144.53
  3459.6 2134.82  3490.3 2152.06  3572.0 2155.05  3623.1 2150.13  3633.3 2138.35
  3673.1 2138.98  3678.2 2134.41  3704.8 2143.81  3796.7 2147.84  3823.1 2141.88
  3858.0 2156.96  3898.9 2146.25  4480.3 2148.19  4559.0 2148.29  4625.8 2147.34
  4661.6 2139.18  4727.0 2145.96  4867.9 2144.88  4927.7 2144.07  4971.1 2141.55
  4992.5 2131.03  4993.4 2130.03  5033.3 2131.03  5053.8 2153.11  5354.8 2162.09
#Mann=8,-1,0
  2553.8   0.035       0  2668.9    0.07       0  4480.3    0.16       0
  4559.0    0.07       0  4867.9    0.16       0  4927.7    0.07       0
  4992.5    0.07       0  5033.3    0.07       0
Bank Sta=4992.5,5033.3
Exp/Cntr=0.3,0.1

Type RM Length L Ch R = 1,239327,327,327,327
BEGIN DESCRIPTION:
Sweetwater Creek 477.0
END DESCRIPTION:
XS GIS Cut Line= 3
      1372467.68      6841747.78      1373911.26      6841739.95
      1374789.80      6841838.06
#Sta/Elev= 30
  3556.4 2181.02  3632.6 2186.77  3653.7 2176.72  3721.1 2166.25  3883.1 2152.62
  4143.7 2150.01  4233.7 2141.27  4283.7 2142.99  4348.4 2138.60  4438.3 2149.26
  4563.7 2146.03  4573.7 2143.82  4583.7 2136.46  4593.7 2136.37  4603.7 2143.88
  4623.7 2144.96  4793.7 2146.27  4823.7 2144.03  4863.7 2135.52  4903.7 2136.30
  4993.7 2131.48  4998.4 2128.38  4999.6 2127.38  5056.0 2128.38  5104.4 2134.66
  5124.5 2142.50  5194.9 2139.61  5217.4 2143.30  5275.4 2146.69  5884.0 2146.75
#Mann=8,-1,0
  3556.4   0.035       0  3632.6    0.07       0  3721.1   0.035       0
  3883.1    0.07       0  4348.4    0.16       0  4998.4    0.07       0
  5056.0    0.16       0  5217.4    0.16       0
Bank Sta=4998.4,5056
Exp/Cntr=0.3,0.1

Type RM Length L Ch R = 1,239000,500,500,500
BEGIN DESCRIPTION:
Sweetwater Creek 476.0
END DESCRIPTION:
XS GIS Cut Line= 3
      1373355.00      6842188.00      1373690.10      6841952.46
      1374584.94      6841864.00
#Sta/Elev= 30
  4590.4 2153.14  4605.9 2152.77  4674.2 2151.59  4871.4 2143.16  4877.5 2145.66
  4898.7 2138.36  4928.0 2133.55  4948.9 2134.91  4978.5 2127.78  5093.2 2139.92
  5098.3 2137.70  5155.7 2154.42  5175.8 2149.46  5194.3 2136.78  5198.9 2142.65
  5205.9 2136.36  5210.1 2119.00  5211.6 2118.00  5282.1 2119.00  5286.3 2124.31
  5295.4 2123.34  5300.4 2127.06  5389.8 2125.08  5427.0 2146.81  5467.2 2148.75
  5507.6 2129.38  5527.5 2134.72  5537.5 2143.88  5547.6 2146.87  5899.2 2145.90
#Mann=8,-1,0
  4590.4   0.035       0  4605.9    0.07       0  4674.2   0.035       0
  4898.7    0.16       0  5198.9    0.07       0  5210.1    0.07       0
  5282.1    0.07       0  5389.8    0.16       0
Bank Sta=5210.1,5282.1
Exp/Cntr=0.3,0.1

Type RM Length L Ch R = 1,238500,780,780,780
BEGIN DESCRIPTION:
Sweetwater Creek 475.0
END DESCRIPTION:
XS GIS Cut Line= 4
      1373554.99      6842638.01      1373767.85      6842400.55
      1373847.64      6842294.91      1374609.65      6841882.78
#Sta/Elev= 30
  4681.1 2154.02  4915.2 2137.33  4957.3 2135.40  4984.9 2126.16  4985.4 2125.16
  5006.5 2126.16  5056.5 2135.30  5141.5 2133.08  5222.3 2133.86  5254.4 2132.38
  5296.9 2141.96  5343.2 2134.30  5348.8 2140.78  5370.7 2143.60  5415.3 2142.91
  5430.7 2136.87  5436.4 2143.78  5452.6 2148.01  5468.7 2137.02  5474.4 2142.66
  5490.6 2133.54  5496.3 2141.10  5512.5 2133.60  5518.2 2141.36  5534.4 2137.02
  5540.1 2142.71  5665.7 2145.23  5697.8 2135.36  5719.9 2145.84  5998.7 2145.94
#Mann=8,-1,0
  4681.1    0.07       0  4915.2    0.16       0  4984.9    0.07       0
  5006.5    0.16       0  5141.5    0.07       0  5222.3    0.16       0
  5296.9    0.07       0  5415.3    0.16       0
Bank Sta=4984.9,5006.5
Exp/Cntr=0.3,0.1

Type RM Length L Ch R = 1,237720,794,794,794
BEGIN DESCRIPTION:
Sweetwater Creek 473.0
END DESCRIPTION:
XS GIS Cut Line= 3
      1374254.97      6843118.12      1374344.57      6842836.95
      1374434.28      6842083.68
#Sta/Elev= 30
  4704.9 2150.46  4914.4 2145.75  4989.3 2137.21  4994.9 2124.44  4995.4 2123.44
  5016.5 2124.44  5050.1 2128.41  5099.7 2126.53  5127.7 2130.53  5132.7 2128.46
  5160.1 2131.04  5338.2 2131.76  5351.4 2133.48  5371.6 2128.24  5401.8 2127.88
  5421.9 2128.87  5442.1 2133.91  5473.0 2126.96  5512.6 2132.18  5542.8 2140.54
  5573.0 2139.39  5593.1 2135.45  5613.3 2141.56  5633.1 2137.50  5683.8 2136.92
  5714.0 2128.19  5725.7 2134.19  5734.1 2143.23  5744.2 2150.07  5758.6 2155.24
#Mann=4,-1,0
  4704.9    0.07       0  4994.9    0.07       0  5016.5    0.07       0
  5338.2    0.16       0
Bank Sta=4994.9,5016.5
Exp/Cntr=0.3,0.1

Type RM Length L Ch R = 1,236926,426,426,426
BEGIN DESCRIPTION:
Sweetwater Creek 472.0
END DESCRIPTION:
XS GIS Cut Line= 3
      1374530.38      6843401.93      1374706.22      6842191.44
      1374605.01      6842038.01
#Sta/Elev= 30
  3776.8 2147.06  3821.2 2145.10  3840.0 2140.54  3985.4 2134.42  4125.7 2134.46
  4245.6 2146.74  4275.9 2130.42  4296.1 2130.33  4316.3 2122.42  4336.5 2120.86
  4377.0 2125.63  4396.2 2134.67  4401.2 2128.48  4407.3 2136.72  4417.4 2142.48
  4611.7 2134.78  4639.7 2129.94  4690.9 2129.96  4720.5 2136.47  4746.9 2130.42
  4771.1 2129.14  4957.4 2127.55  4983.3 2123.37  4989.0 2119.52  4989.4 2118.52
  5010.6 2119.52  5046.8 2129.00  5076.0 2129.31  5147.9 2143.37  5183.8 2144.51
#Mann=4,-1,0
  3776.8    0.07       0  4690.9    0.16       0  4989.0    0.07       0
  5010.6    0.16       0
Bank Sta=4989,5010.6
Exp/Cntr=0.3,0.1

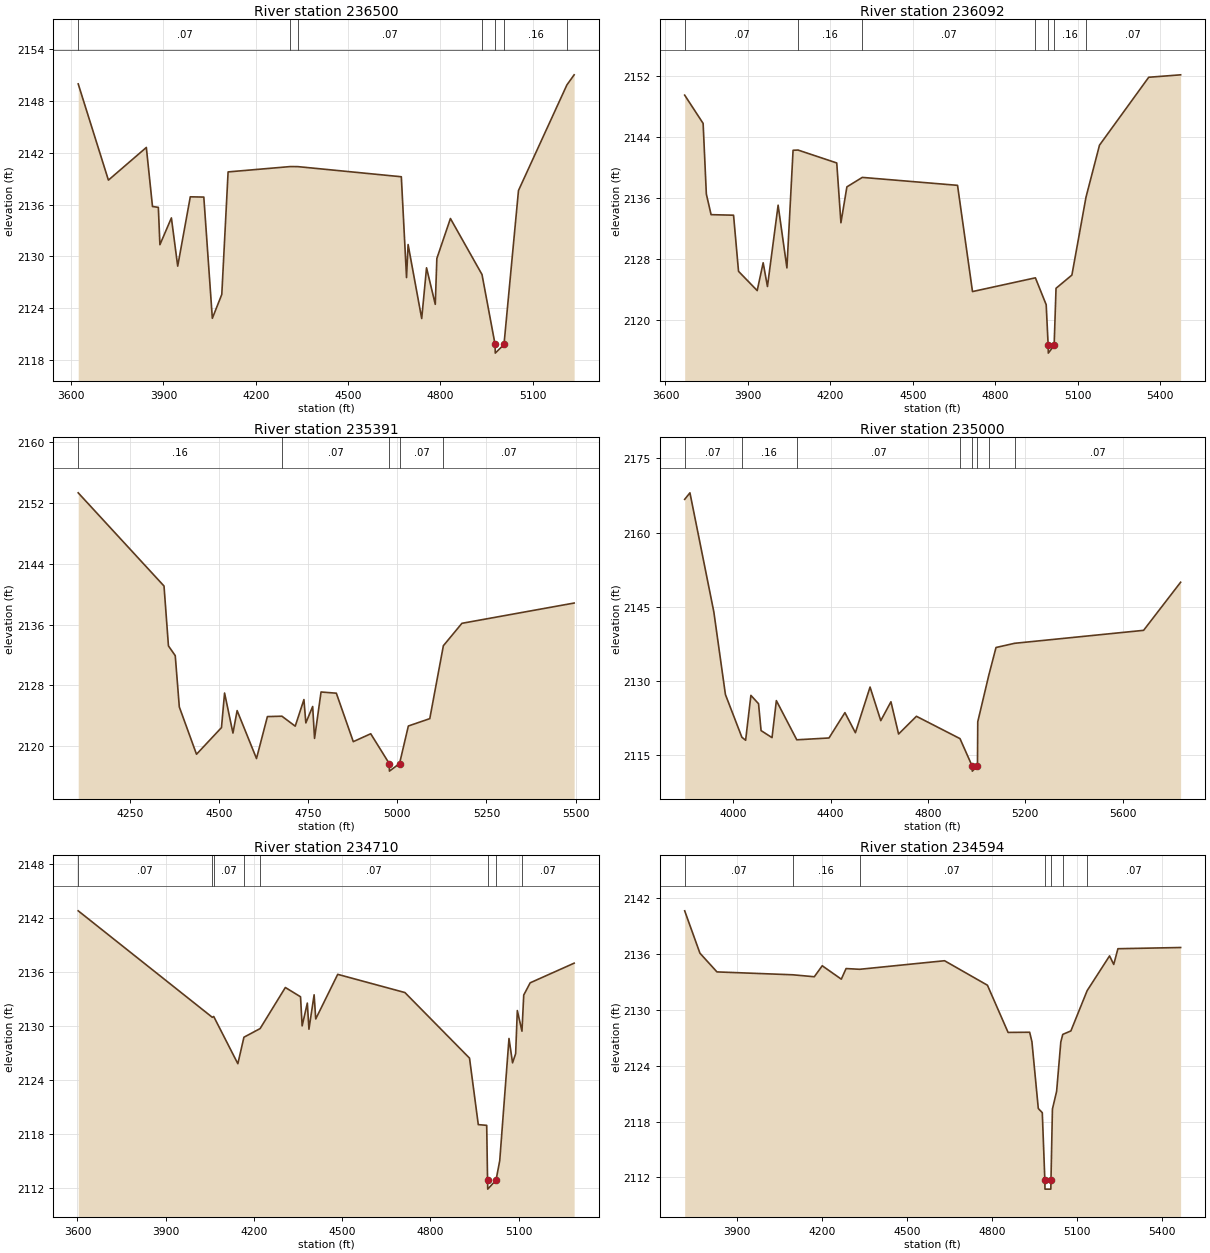
Type RM Length L Ch R = 1,236500,408,408,408
BEGIN DESCRIPTION:
Sweetwater Creek 471.0
END DESCRIPTION:
XS GIS Cut Line= 3
      1374834.20      6843553.89      1375125.22      6842208.40
      1375205.00      6841988.00
#Sta/Elev= 30
  3623.4 2149.95  3721.5 2138.82  3844.7 2142.60  3864.7 2135.77  3883.7 2135.67
  3888.8 2131.35  3926.1 2134.45  3946.6 2128.87  3987.5 2136.89  4031.4 2136.86
  4059.1 2122.84  4089.8 2125.60  4110.3 2139.77  4312.8 2140.39  4337.2 2140.38
  4673.0 2139.21  4689.9 2127.55  4695.0 2131.37  4739.2 2122.81  4754.9 2128.68
  4783.3 2124.45  4788.4 2129.76  4832.5 2134.38  4935.1 2127.90  4977.6 2119.81
  4978.2 2118.81  5006.5 2119.81  5053.6 2137.62  5210.8 2149.83  5234.4 2151.00
#Mann=7,-1,0
  3623.4    0.07       0  4312.8    0.16       0  4337.2    0.07       0
  4935.1    0.16       0  4977.6    0.07       0  5006.5    0.16       0
  5210.8    0.07       0
Bank Sta=4977.6,5006.5
Exp/Cntr=0.3,0.1

Type RM Length L Ch R = 1,236092,701,701,701
BEGIN DESCRIPTION:
Sweetwater Creek 470.0
END DESCRIPTION:
XS GIS Cut Line= 3
      1374981.77      6843510.48      1375505.35      6842287.65
      1375655.00      6841838.00
#Sta/Elev= 30
  3669.8 2149.47  3736.9 2145.77  3748.6 2136.52  3765.9 2133.82  3847.6 2133.75
  3865.7 2126.40  3933.6 2123.88  3955.3 2127.52  3970.9 2124.41  4009.7 2135.06
  4041.7 2126.85  4064.1 2142.25  4082.3 2142.28  4223.0 2140.59  4238.2 2132.76
  4259.9 2137.46  4316.0 2138.70  4662.4 2137.66  4716.8 2123.75  4945.6 2125.55
  4984.9 2122.03  4992.1 2116.69  4992.6 2115.69  5013.8 2116.69  5020.7 2124.18
  5078.4 2125.91  5129.7 2136.11  5178.8 2142.92  5357.9 2151.81  5473.9 2152.13
#Mann=7,-1,0
  3669.8    0.07       0  4082.3    0.16       0  4316.0    0.07       0
  4945.6    0.16       0  4992.1    0.07       0  5013.8    0.16       0
  5129.7    0.07       0
Bank Sta=4992.1,5013.8
Exp/Cntr=0.3,0.1

Type RM Length L Ch R = 1,235391,391,391,391
BEGIN DESCRIPTION:
Sweetwater Creek 469.0
END DESCRIPTION:
XS GIS Cut Line= 3
      1375389.13      6843672.02      1375715.33      6842838.79
      1375745.90      6842343.94
#Sta/Elev= 30
  4105.2 2153.34  4345.8 2141.07  4358.2 2133.19  4377.3 2131.90  4388.7 2125.15
  4436.9 2118.92  4506.9 2122.43  4515.6 2126.98  4539.1 2121.71  4550.8 2124.67
  4605.1 2118.36  4635.7 2123.88  4676.4 2123.93  4713.7 2122.62  4738.1 2126.12
  4743.5 2123.05  4762.6 2125.21  4767.9 2121.01  4786.1 2127.12  4829.0 2126.96
  4876.5 2120.58  4925.4 2121.62  4977.3 2117.70  4977.9 2116.70  5006.2 2117.70
  5030.9 2122.64  5091.0 2123.61  5129.1 2133.21  5181.1 2136.16  5495.8 2138.83
#Mann=5,-1,0
  4105.2    0.16       0  4676.4    0.07       0  4977.3    0.07       0
  5006.2    0.07       0  5129.1    0.07       0
Bank Sta=4977.3,5006.2
Exp/Cntr=0.3,0.1

Type RM Length L Ch R = 1,235000,290,290,290
BEGIN DESCRIPTION:
Sweetwater Creek 468.0
END DESCRIPTION:
XS GIS Cut Line= 3
      1375654.99      6843738.02      1376007.93      6842591.52
      1375686.38      6841817.55
#Sta/Elev= 30
  3800.4 2166.73  3822.0 2168.05  3920.1 2144.02  3967.8 2127.29  4035.4 2118.66
  4050.8 2118.05  4072.5 2127.12  4103.9 2125.43  4114.3 2120.00  4159.3 2118.58
  4177.1 2126.06  4261.0 2118.14  4393.4 2118.51  4458.8 2123.63  4501.9 2119.57
  4562.1 2128.80  4606.1 2122.01  4647.9 2125.83  4679.3 2119.31  4752.6 2122.89
  4931.6 2118.38  4981.8 2112.81  4982.2 2111.81  5003.4 2112.81  5004.6 2121.78
  5049.7 2131.14  5079.6 2136.79  5155.8 2137.64  5686.0 2140.26  5838.1 2149.98
#Mann=8,-1,0
  3800.4    0.07       0  4035.4    0.16       0  4261.0    0.07       0
  4931.6    0.16       0  4981.8    0.07       0  5003.4    0.16       0
  5049.7    0.16       0  5155.8    0.07       0
Bank Sta=4981.8,5003.4
Exp/Cntr=0.3,0.1

Type RM Length L Ch R = 1,234710,116,116,116
BEGIN DESCRIPTION:
Sweetwater Creek 4097
END DESCRIPTION:
XS GIS Cut Line= 3
      1376843.52      6843859.16      1376265.55      6842586.89
      1376127.55      6842333.43
#Sta/Elev= 30
  3602.6 2142.79  4058.5 2130.97  4063.3 2131.06  4145.3 2125.82  4166.0 2128.76
  4221.0 2129.72  4306.8 2134.28  4358.4 2133.25  4363.9 2130.02  4381.5 2132.55
  4387.0 2129.65  4404.6 2133.47  4410.1 2130.79  4484.8 2135.74  4713.2 2133.72
  4932.9 2126.44  4962.7 2119.06  4991.3 2118.98  4994.2 2112.90  4994.8 2111.90
  5023.0 2112.90  5035.6 2115.05  5067.1 2128.62  5079.2 2125.92  5089.7 2126.93
  5095.4 2131.72  5111.2 2129.43  5117.2 2133.44  5139.1 2134.80  5288.6 2136.98
#Mann=8,-1,0
  3602.6    0.07       0  4058.5    0.16       0  4063.3    0.07       0
  4166.0    0.16       0  4221.0    0.07       0  4994.2    0.07       0
  5023.0    0.07       0  5111.2    0.07       0
Bank Sta=4994.2,5023
Exp/Cntr=0.3,0.1

Type RM Length L Ch R = 1,234594,541,541,541
BEGIN DESCRIPTION:
Sweetwater Creek 467.0
END DESCRIPTION:
XS GIS Cut Line= 3
      1376944.47      6843720.16      1376374.95      6842567.93
      1376104.98      6842187.97
#Sta/Elev= 30
  3714.7 2140.64  3768.6 2136.09  3828.7 2134.08  4096.4 2133.77  4172.5 2133.56
  4200.5 2134.74  4267.8 2133.30  4284.7 2134.44  4332.6 2134.36  4632.4 2135.28
  4783.9 2132.65  4856.8 2127.58  4933.0 2127.60  4941.0 2126.58  4963.5 2119.41
  4977.6 2118.96  4986.6 2111.75  4987.1 2110.75  5007.8 2110.75  5008.3 2111.75
  5013.4 2119.35  5028.2 2121.25  5043.0 2126.55  5049.9 2127.37  5078.6 2127.74
  5135.9 2132.06  5215.2 2135.80  5229.9 2134.88  5244.7 2136.57  5466.1 2136.70
#Mann=7,-1,0
  3714.7    0.07       0  4096.4    0.16       0  4332.6    0.07       0
  4986.6    0.07       0  5008.3    0.07       0  5049.9    0.16       0
  5135.9    0.07       0
Bank Sta=4986.6,5008.3
Exp/Cntr=0.3,0.1

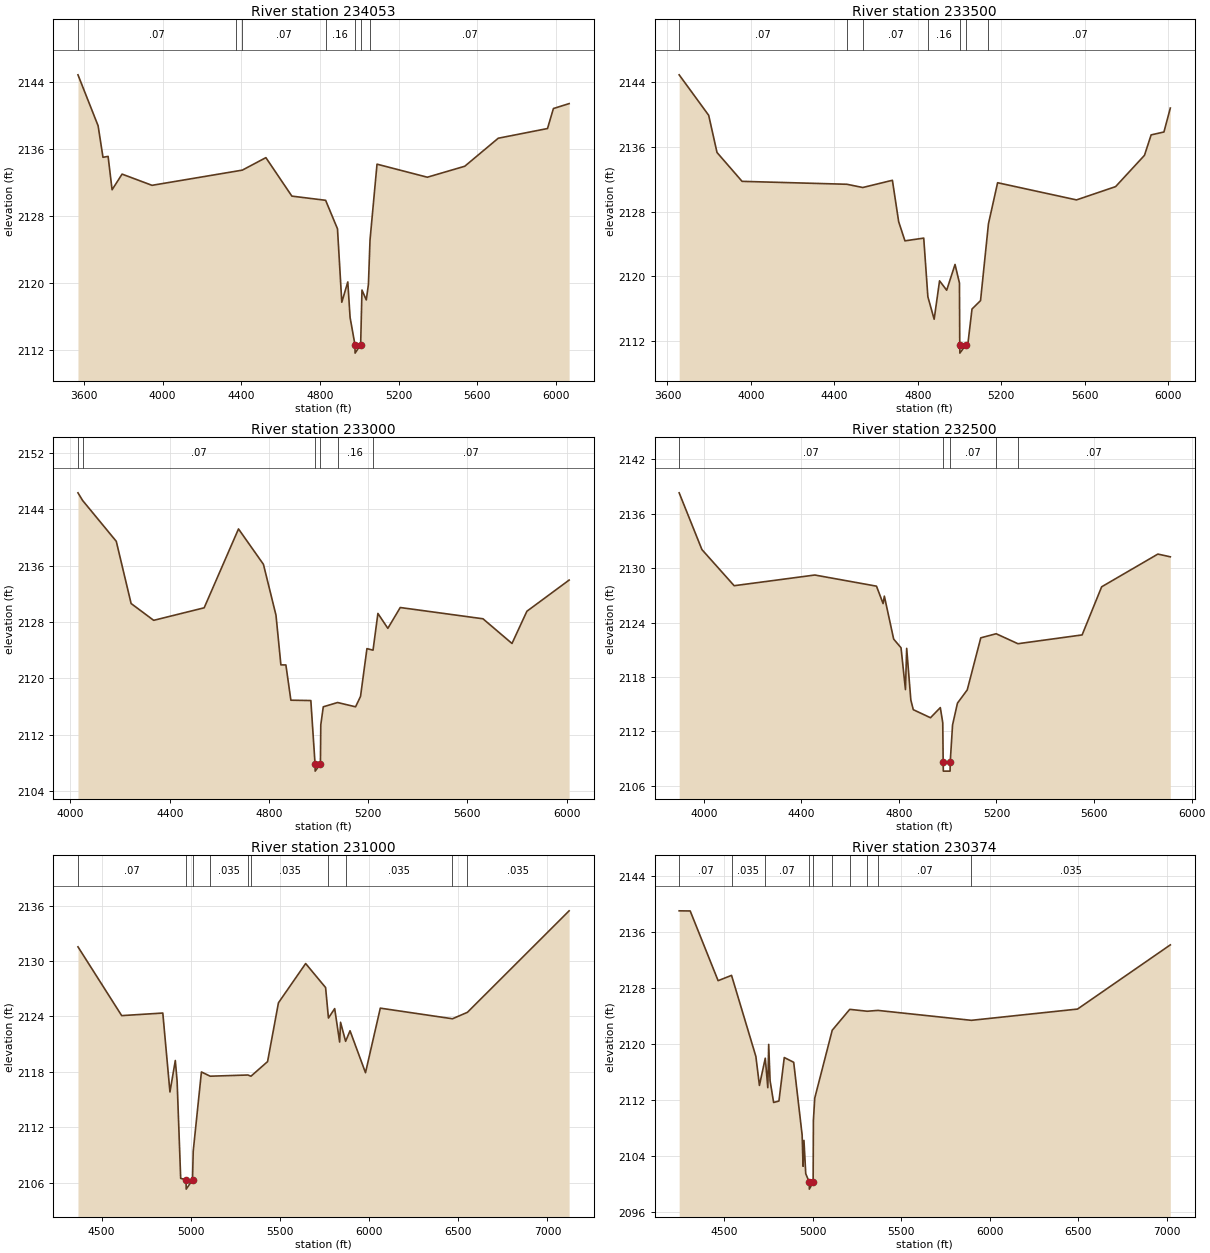
Type RM Length L Ch R = 1,234053,553,553,553
BEGIN DESCRIPTION:
Sweetwater Creek 466.0
END DESCRIPTION:
XS GIS Cut Line= 4
      1377092.23      6843758.78      1376841.27      6842350.98
      1376778.37      6842208.76      1376832.39      6841298.27
#Sta/Elev= 30
  3570.0 2144.86  3672.4 2138.77  3697.2 2135.00  3723.2 2135.11  3743.5 2131.12
  3794.3 2132.99  3946.6 2131.65  4371.5 2133.33  4406.1 2133.47  4525.6 2134.96
  4657.7 2130.36  4829.4 2129.86  4889.7 2126.45  4911.6 2117.67  4942.1 2120.10
  4953.8 2115.85  4978.6 2112.59  4979.2 2111.59  5007.5 2112.59  5014.2 2119.13
  5036.1 2117.95  5047.0 2119.80  5055.1 2125.10  5090.7 2134.18  5346.6 2132.62
  5536.9 2133.93  5707.2 2137.28  5957.7 2138.44  5987.7 2140.83  6067.6 2141.42
#Mann=7,-1,0
  3570.0    0.07       0  4371.5    0.16       0  4406.1    0.07       0
  4829.4    0.16       0  4978.6    0.07       0  5007.5    0.16       0
  5055.1    0.07       0
Bank Sta=4978.6,5007.5
Exp/Cntr=0.3,0.1

Type RM Length L Ch R = 1,233500,500,500,500
BEGIN DESCRIPTION:
Sweetwater Creek 465.0
END DESCRIPTION:
XS GIS Cut Line= 3
      1377231.95      6843769.30      1377294.39      6842426.86
      1377504.99      6841438.03
#Sta/Elev= 30
  3656.1 2144.87  3797.6 2139.88  3837.6 2135.29  3957.7 2131.73  4460.2 2131.37
  4536.4 2130.97  4678.5 2131.86  4708.5 2126.76  4738.6 2124.39  4828.7 2124.73
  4848.6 2117.49  4878.7 2114.72  4904.6 2119.46  4938.8 2118.30  4978.8 2121.48
  5000.0 2119.19  5001.4 2111.54  5002.0 2110.54  5030.3 2111.54  5039.7 2111.54
  5060.2 2115.98  5101.1 2117.02  5139.0 2126.49  5182.9 2131.56  5561.2 2129.44
  5748.7 2131.08  5887.1 2134.94  5919.0 2137.46  5980.4 2137.82  6011.0 2140.77
#Mann=7,-1,0
  3656.1    0.07       0  4460.2    0.16       0  4536.4    0.07       0
  4848.6    0.16       0  5001.4    0.07       0  5030.3    0.16       0
  5139.0    0.07       0
Bank Sta=5001.4,5030.3
Exp/Cntr=0.3,0.1

Type RM Length L Ch R = 1,233000,500,500,500
BEGIN DESCRIPTION:
Sweetwater Creek 464.0
END DESCRIPTION:
XS GIS Cut Line= 3
      1377812.85      6843611.52      1377711.59      6842647.03
      1377755.00      6841637.96
#Sta/Elev= 30
  4030.2 2146.35  4049.0 2145.26  4184.6 2139.46  4244.4 2130.62  4335.4 2128.23
  4538.9 2130.01  4677.3 2141.22  4777.8 2136.19  4828.4 2128.96  4848.2 2121.90
  4868.3 2121.89  4888.4 2116.88  4968.9 2116.83  4985.9 2107.80  4986.3 2106.80
  5007.5 2107.80  5009.0 2113.38  5019.0 2115.94  5076.7 2116.55  5149.2 2115.94
  5169.2 2117.42  5195.0 2124.21  5219.6 2123.99  5239.2 2129.21  5279.3 2127.09
  5329.3 2130.05  5662.8 2128.45  5779.7 2124.94  5839.8 2129.52  6010.0 2133.95
#Mann=6,-1,0
  4030.2   0.035       0  4049.0    0.07       0  4985.9    0.07       0
  5007.5    0.07       0  5076.7    0.16       0  5219.6    0.07       0
Bank Sta=4985.9,5007.5
Exp/Cntr=0.3,0.1

Type RM Length L Ch R = 1,232500,1500,1500,1500
BEGIN DESCRIPTION:
Sweetwater Creek 463.0
END DESCRIPTION:
XS GIS Cut Line= 3
      1377999.56      6843582.10      1378118.36      6842487.93
      1378062.38      6841577.15
#Sta/Elev= 30
  3899.4 2138.32  3992.6 2132.06  4124.8 2128.07  4455.5 2129.25  4708.2 2128.02
  4735.3 2126.10  4740.4 2126.92  4778.6 2122.18  4808.8 2121.22  4826.9 2116.61
  4831.9 2121.16  4849.0 2115.45  4859.1 2114.39  4929.5 2113.50  4969.8 2114.62
  4979.8 2112.95  4981.5 2108.61  4982.1 2107.61  5009.8 2107.61  5010.4 2108.61
  5020.0 2112.71  5040.0 2115.11  5080.1 2116.57  5135.7 2122.32  5198.7 2122.77
  5287.9 2121.67  5551.0 2122.64  5631.1 2127.95  5861.5 2131.56  5912.5 2131.26
#Mann=5,-1,0
  3899.4    0.07       0  4981.5    0.07       0  5010.4    0.07       0
  5198.7   0.035       0  5287.9    0.07       0
Bank Sta=4981.5,5010.4
Exp/Cntr=0.3,0.1

Type RM Length L Ch R = 1,231000,626,626,626
BEGIN DESCRIPTION:
Sweetwater Creek 460.0
END DESCRIPTION:
XS GIS Cut Line= 3
      1378770.39      6843922.67      1378809.14      6843291.76
      1379191.32      6841205.17
#Sta/Elev= 30
  4367.9 2131.54  4613.0 2124.09  4843.5 2124.37  4883.5 2115.82  4913.6 2119.23
  4923.6 2117.02  4943.7 2106.47  4973.8 2106.30  4974.6 2105.30  5010.0 2106.30
  5014.0 2109.41  5060.0 2117.99  5109.2 2117.53  5320.5 2117.66  5337.8 2117.53
  5430.8 2119.11  5491.8 2125.48  5644.3 2129.73  5756.1 2127.13  5772.1 2123.83
  5807.0 2124.85  5834.9 2121.23  5839.9 2123.37  5868.3 2121.31  5893.1 2122.45
  5979.8 2117.91  6062.8 2124.90  6467.4 2123.75  6551.3 2124.45  7121.3 2135.44
#Mann=10,-1,0
  4367.9    0.07       0  4973.8    0.07       0  5010.0    0.07       0
  5109.2   0.035       0  5320.5    0.07       0  5337.8   0.035       0
  5772.1    0.07       0  5868.3   0.035       0  6467.4    0.07       0
  6551.3   0.035       0
Bank Sta=4973.8,5010
Exp/Cntr=0.3,0.1

Type RM Length L Ch R = 1,230374,277,277,277
BEGIN DESCRIPTION:
Sweetwater Creek 459.0
END DESCRIPTION:
XS GIS Cut Line= 3
      1379204.15      6843790.10      1379250.12      6843146.94
      1379631.96      6841052.36
#Sta/Elev= 30
  4245.4 2139.01  4307.7 2138.99  4465.4 2129.02  4541.2 2129.78  4678.6 2118.19
  4698.7 2114.04  4731.7 2117.93  4746.0 2113.72  4751.0 2119.91  4758.8 2114.73
  4778.9 2111.60  4808.9 2111.81  4839.0 2118.03  4892.2 2117.35  4939.9 2106.96
  4945.2 2102.48  4950.2 2106.18  4960.3 2101.41  4980.3 2100.21  4980.7 2099.21
  5002.0 2100.21  5003.5 2109.02  5011.1 2112.22  5109.8 2121.93  5208.8 2124.92
  5307.9 2124.65  5367.4 2124.77  5895.8 2123.35  6495.2 2124.96  7019.3 2134.14
#Mann=10,-1,0
  4245.4    0.07       0  4541.2   0.035       0  4731.7    0.07       0
  4980.3    0.07       0  5002.0    0.07       0  5109.8   0.035       0
  5208.8    0.07       0  5307.9   0.035       0  5367.4    0.07       0
  5895.8   0.035       0
Bank Sta=4980.3,5002
Exp/Cntr=0.3,0.1

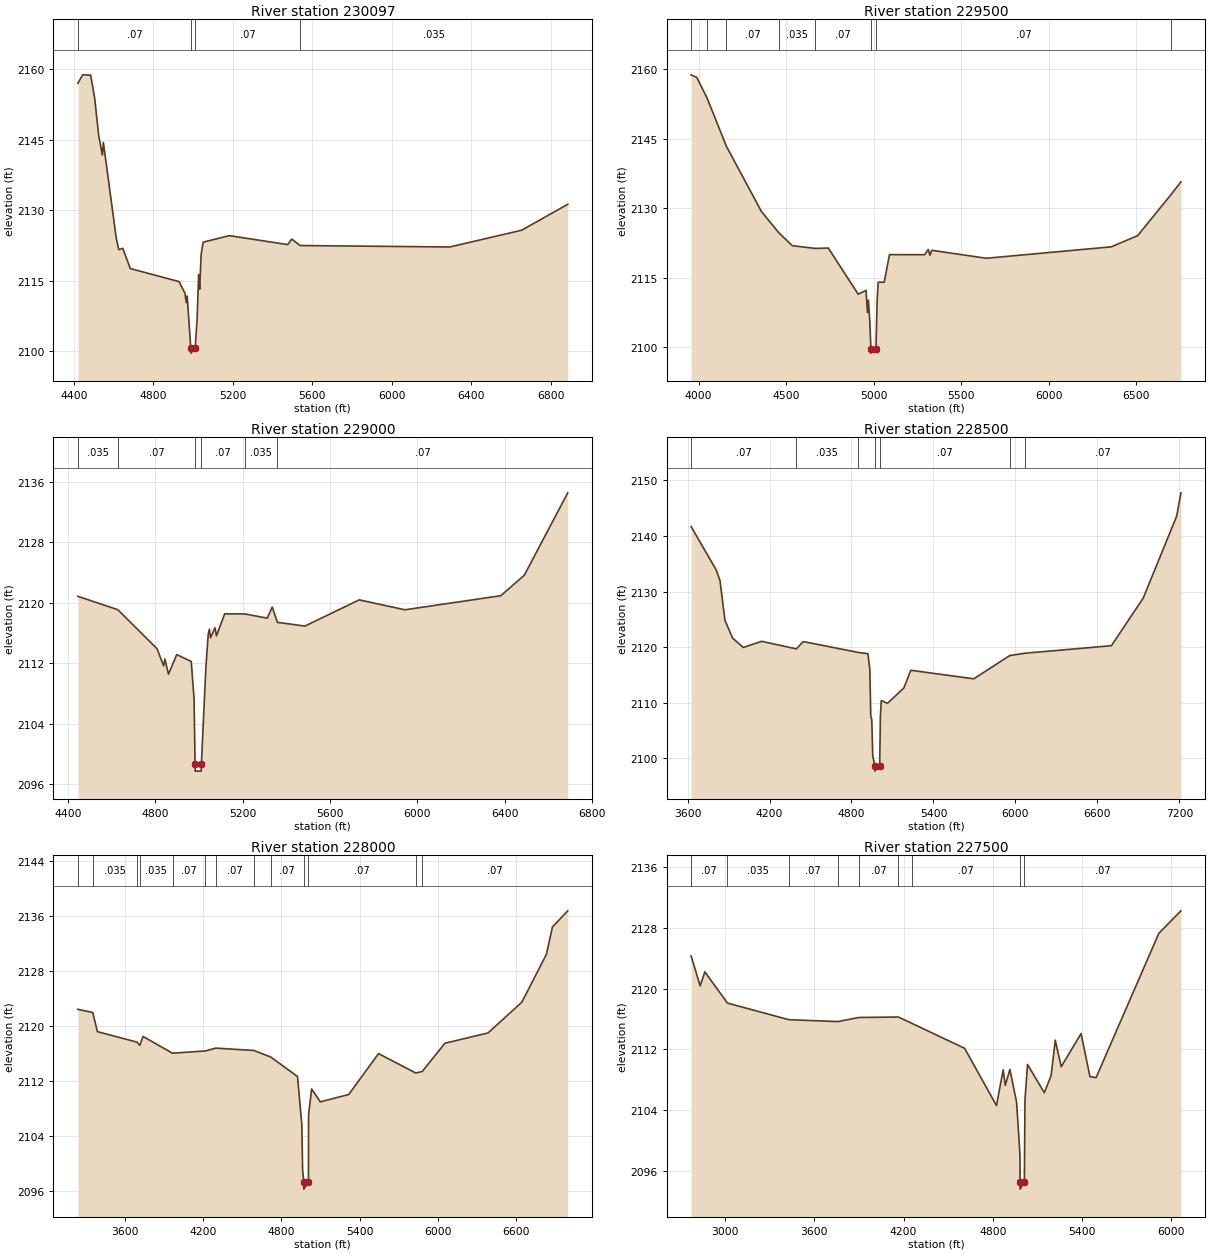
Type RM Length L Ch R = 1,230097,597,597,597
BEGIN DESCRIPTION:
Sweetwater Creek 458.0
END DESCRIPTION:
XS GIS Cut Line= 3
      1379441.95      6843541.66      1379524.89      6842967.73
      1379839.23      6841108.41
#Sta/Elev= 30
  4420.1 2156.97  4444.0 2158.76  4484.4 2158.69  4504.6 2153.77  4524.8 2145.83
  4543.2 2141.70  4548.2 2144.40  4613.5 2123.89  4625.9 2121.57  4646.1 2121.84
  4683.8 2117.54  4929.0 2114.77  4959.3 2112.29  4965.1 2110.31  4970.2 2111.71
  4988.3 2100.55  4988.8 2099.55  5010.1 2100.55  5020.0 2106.65  5027.9 2116.27
  5032.9 2113.17  5040.3 2120.53  5050.4 2123.16  5182.3 2124.54  5476.4 2122.64
  5496.7 2123.81  5538.9 2122.44  6291.6 2122.13  6654.1 2125.70  6885.7 2131.21
#Mann=4,-1,0
  4420.1    0.07       0  4988.3    0.07       0  5010.1    0.07       0
  5538.9   0.035       0
Bank Sta=4988.3,5010.1
Exp/Cntr=0.3,0.1

Type RM Length L Ch R = 1,229500,500,500,500
BEGIN DESCRIPTION:
Sweetwater Creek 457.0
END DESCRIPTION:
XS GIS Cut Line= 3
      1379654.98      6843738.04      1380062.86      6842778.10
      1379874.01      6841032.48
#Sta/Elev= 30
  3957.0 2158.82  3989.6 2158.26  4048.2 2153.81  4158.7 2143.38  4359.1 2129.26
  4458.4 2124.67  4535.4 2121.88  4666.4 2121.29  4740.9 2121.37  4911.9 2111.39
  4956.6 2112.23  4964.6 2107.41  4970.0 2110.09  4978.4 2105.32  4984.4 2099.65
  4985.0 2098.65  5013.4 2099.65  5020.2 2110.23  5025.9 2113.98  5060.4 2113.98
  5090.6 2119.94  5291.8 2119.93  5311.9 2121.06  5322.0 2119.82  5332.0 2120.88
  5643.8 2119.16  6358.0 2121.63  6508.9 2124.06  6699.7 2132.95  6755.8 2135.68
#Mann=8,-1,0
  3957.0    0.07       0  4048.2   0.035       0  4158.7    0.07       0
  4458.4   0.035       0  4666.4    0.07       0  4984.4    0.07       0
  5013.4    0.07       0  6699.7   0.035       0
Bank Sta=4984.4,5013.4
Exp/Cntr=0.3,0.1

Type RM Length L Ch R = 1,229000,500,500,500
BEGIN DESCRIPTION:
Sweetwater Creek 456.0
END DESCRIPTION:
XS GIS Cut Line= 3
      1380255.00      6843137.99      1380514.49      6842648.63
      1380009.70      6841036.51
#Sta/Elev= 30
  4446.1 2120.84  4628.9 2119.07  4808.3 2113.93  4838.8 2111.64  4844.5 2112.55
  4860.8 2110.56  4898.8 2113.14  4965.1 2112.24  4978.1 2107.28  4982.6 2098.75
  4983.2 2097.75  5011.0 2097.75  5011.6 2098.75  5032.1 2111.41  5042.6 2115.77
  5048.2 2116.50  5053.4 2115.36  5074.0 2116.69  5080.6 2115.62  5118.3 2118.53
  5210.4 2118.51  5313.0 2117.96  5336.0 2119.42  5360.0 2117.40  5485.7 2116.91
  5734.2 2120.37  5943.8 2119.06  6382.9 2120.92  6490.7 2123.64  6689.3 2134.51
#Mann=6,-1,0
  4446.1   0.035       0  4628.9    0.07       0  4982.6    0.07       0
  5011.6    0.07       0  5210.4   0.035       0  5360.0    0.07       0
Bank Sta=4982.6,5011.6
Exp/Cntr=0.3,0.1

Type RM Length L Ch R = 1,228500,500,500,500
BEGIN DESCRIPTION:
Sweetwater Creek 455.0
END DESCRIPTION:
XS GIS Cut Line= 3
      1379954.99      6843788.01      1380948.09      6842838.18
      1380004.99      6840837.97
#Sta/Elev= 30
  3625.8 2141.70  3809.6 2133.89  3837.9 2131.92  3873.5 2124.81  3930.1 2121.60
  4007.8 2119.93  4142.1 2121.03  4397.0 2119.67  4446.2 2120.99  4850.4 2119.03
  4920.2 2118.80  4934.3 2116.00  4941.2 2107.52  4948.5 2106.92  4955.4 2100.46
  4970.3 2098.66  4971.1 2097.66  5006.5 2098.66  5011.3 2107.45  5017.9 2110.36
  5063.4 2109.87  5182.9 2112.61  5234.0 2115.82  5695.1 2114.28  5957.7 2118.46
  6069.3 2118.89  6702.3 2120.24  6935.0 2128.79  7180.0 2143.55  7211.4 2147.77
#Mann=7,-1,0
  3625.8    0.07       0  4397.0   0.035       0  4850.4    0.07       0
  4970.3    0.07       0  5006.5    0.07       0  5957.7    0.16       0
  6069.3    0.07       0
Bank Sta=4970.3,5006.5
Exp/Cntr=0.3,0.1

Type RM Length L Ch R = 1,228000,500,500,500
BEGIN DESCRIPTION:
Sweetwater Creek 454.0
END DESCRIPTION:
XS GIS Cut Line= 4
      1381096.54      6844261.03      1381439.90      6842786.45
      1381334.45      6842558.60      1380533.06      6840724.97
#Sta/Elev= 30
  3234.9 2122.41  3349.1 2121.94  3384.7 2119.16  3689.2 2117.63  3711.2 2117.17
  3735.6 2118.46  3962.3 2116.02  4215.6 2116.35  4294.3 2116.76  4587.1 2116.42
  4718.6 2115.45  4923.5 2112.63  4956.6 2105.60  4962.5 2099.13  4971.2 2097.24
  4972.0 2096.24  5007.4 2097.24  5008.6 2107.08  5032.0 2110.81  5098.9 2108.94
  5317.1 2110.01  5546.3 2115.96  5832.7 2113.14  5882.4 2113.36  6056.8 2117.47
  6388.3 2118.97  6648.6 2123.45  6836.7 2130.39  6883.5 2134.39  7001.1 2136.74
#Mann=13,-1,0
  3234.9    0.07       0  3349.1   0.035       0  3689.2    0.07       0
  3711.2   0.035       0  3962.3    0.07       0  4215.6   0.035       0
  4294.3    0.07       0  4587.1   0.035       0  4718.6    0.07       0
  4971.2    0.07       0  5007.4    0.07       0  5832.7   0.035       0
  5882.4    0.07       0
Bank Sta=4971.2,5007.4
Exp/Cntr=0.3,0.1

Type RM Length L Ch R = 1,227500,500,500,500
BEGIN DESCRIPTION:
Sweetwater Creek 453.0
END DESCRIPTION:
XS GIS Cut Line= 5
      1381279.33      6844299.30      1381607.68      6842319.35
      1381504.65      6842122.47      1381345.49      6841790.77
      1381174.62      6841115.05
#Sta/Elev= 30
  2770.8 2124.32  2832.0 2120.37  2863.3 2122.22  3015.3 2118.11  3427.6 2115.92
  3757.4 2115.67  3899.2 2116.21  4164.9 2116.27  4258.5 2115.41  4610.3 2112.15
  4824.5 2104.61  4869.6 2109.32  4883.6 2107.27  4914.8 2109.37  4959.9 2105.03
  4982.5 2098.11  4983.1 2094.60  4983.7 2093.60  5012.1 2094.60  5016.2 2105.37
  5033.3 2110.02  5146.5 2106.30  5191.8 2108.55  5220.0 2113.22  5259.8 2109.72
  5393.4 2114.09  5453.3 2108.41  5494.5 2108.29  5916.4 2127.30  6064.9 2130.26
#Mann=9,-1,0
  2770.8    0.07       0  3015.3   0.035       0  3427.6    0.07       0
  3757.4   0.035       0  3899.2    0.07       0  4164.9   0.035       0
  4258.5    0.07       0  4983.1    0.07       0  5012.1    0.07       0
Bank Sta=4983.1,5012.1
Exp/Cntr=0.3,0.1

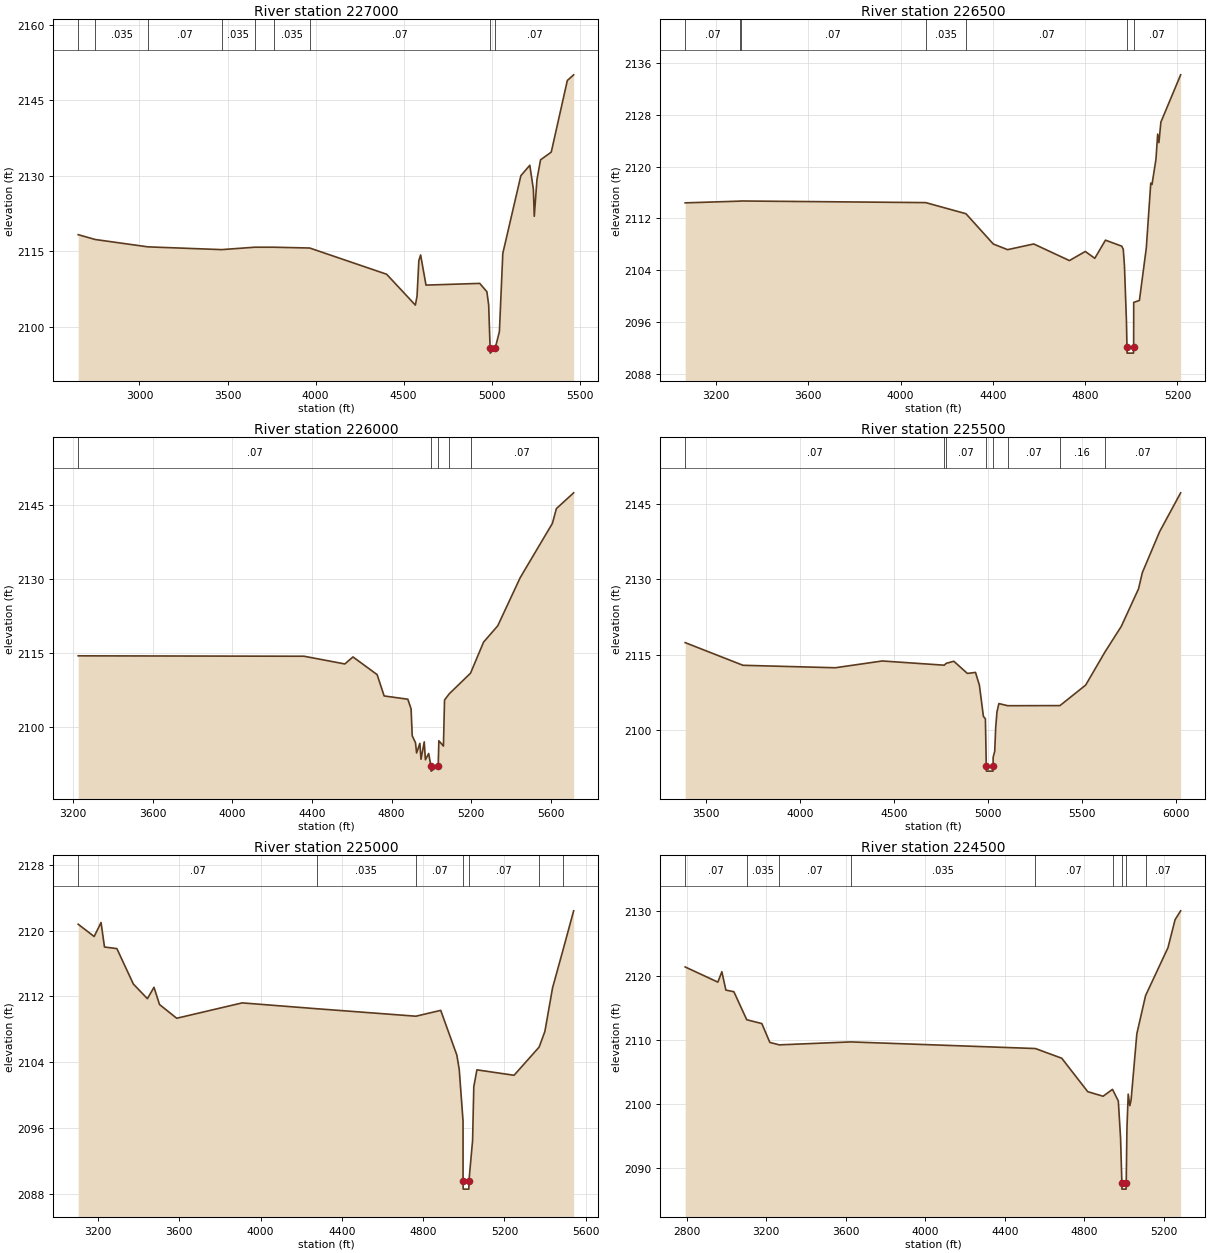
Type RM Length L Ch R = 1,227000,500,500,500
BEGIN DESCRIPTION:
Sweetwater Creek 452.0
END DESCRIPTION:
XS GIS Cut Line= 3
      1381377.74      6844140.66      1381798.53      6841830.87
      1381878.34      6841372.77
#Sta/Elev= 30
  2652.2 2118.30  2749.3 2117.34  3048.1 2115.88  3466.7 2115.33  3654.6 2115.81
  3762.3 2115.81  3966.6 2115.65  4403.2 2110.44  4566.4 2104.31  4576.0 2106.11
  4586.2 2113.16  4596.3 2114.27  4626.8 2108.28  4931.8 2108.62  4972.4 2106.97
  4982.6 2104.34  4990.8 2095.76  4991.4 2094.76  5019.8 2095.76  5043.5 2099.03
  5062.8 2114.58  5165.3 2130.02  5216.1 2132.10  5236.4 2127.33  5241.5 2121.96
  5256.7 2129.24  5277.0 2133.17  5337.9 2134.71  5429.2 2148.95  5465.0 2150.07
#Mann=9,-1,0
  2652.2    0.07       0  2749.3   0.035       0  3048.1    0.07       0
  3466.7   0.035       0  3654.6    0.07       0  3762.3   0.035       0
  3966.6    0.07       0  4990.8    0.07       0  5019.8    0.07       0
Bank Sta=4990.8,5019.8
Exp/Cntr=0.3,0.1

Type RM Length L Ch R = 1,226500,500,500,500
BEGIN DESCRIPTION:
Sweetwater Creek 451.0
END DESCRIPTION:
XS GIS Cut Line= 3
      1381656.90      6844063.87      1382128.08      6842187.83
      1382204.99      6841988.02
#Sta/Elev= 30
  3065.7 2114.41  3305.1 2114.68  3307.3 2114.70  4108.4 2114.45  4283.2 2112.73
  4401.8 2108.04  4463.7 2107.17  4577.1 2108.05  4731.8 2105.48  4800.7 2106.89
  4841.8 2105.83  4888.1 2108.64  4958.6 2107.71  4965.3 2107.24  4970.4 2104.75
  4979.2 2096.00  4981.3 2092.16  4981.9 2091.16  5009.7 2091.16  5010.3 2092.16
  5010.6 2099.01  5035.3 2099.31  5065.2 2107.43  5084.5 2117.46  5089.9 2117.25
  5107.0 2121.14  5114.5 2125.05  5119.9 2123.73  5128.4 2126.90  5214.1 2134.22
#Mann=7,-1,0
  3065.7    0.07       0  3305.1   0.035       0  3307.3    0.07       0
  4108.4   0.035       0  4283.2    0.07       0  4981.3    0.07       0
  5010.3    0.07       0
Bank Sta=4981.3,5010.3
Exp/Cntr=0.3,0.1

Type RM Length L Ch R = 1,226000,500,500,500
BEGIN DESCRIPTION:
Sweetwater Creek 450.0
END DESCRIPTION:
XS GIS Cut Line= 5
      1381861.20      6844316.45      1382179.84      6842845.79
      1382304.98      6842607.99      1382405.00      6842388.00
      1382487.53      6841922.72
#Sta/Elev= 30
  3226.5 2114.48  4360.7 2114.40  4565.3 2112.84  4606.2 2114.26  4727.6 2110.68
  4762.7 2106.37  4881.6 2105.71  4898.0 2103.76  4903.7 2098.32  4920.1 2096.91
  4925.7 2094.84  4942.1 2096.79  4947.7 2093.57  4964.1 2097.09  4969.8 2093.47
  4986.2 2094.74  4997.8 2092.17  4998.6 2091.17  5034.1 2092.17  5037.4 2097.31
  5060.4 2096.24  5065.9 2105.54  5089.4 2106.80  5196.4 2110.97  5262.0 2117.26
  5333.1 2120.55  5446.0 2130.30  5607.3 2141.25  5627.6 2144.25  5714.2 2147.44
#Mann=5,-1,0
  3226.5    0.07       0  4997.8    0.07       0  5034.1    0.07       0
  5089.4    0.16       0  5196.4    0.07       0
Bank Sta=4997.8,5034.1
Exp/Cntr=0.3,0.1

Type RM Length L Ch R = 1,225500,500,500,500
BEGIN DESCRIPTION:
Sweetwater Creek 449.0
END DESCRIPTION:
XS GIS Cut Line= 3
      1381965.79      6844577.75      1382462.82      6843044.07
      1382655.01      6842037.96
#Sta/Elev= 30
  3387.8 2117.37  3695.5 2112.85  4186.4 2112.36  4436.5 2113.71  4766.1 2112.87
  4777.0 2113.24  4817.2 2113.66  4889.5 2111.23  4932.8 2111.43  4953.5 2108.87
  4974.8 2102.65  4985.4 2102.18  4990.1 2092.74  4990.8 2091.74  5025.6 2091.74
  5026.4 2092.74  5026.5 2094.49  5035.0 2095.70  5040.1 2100.42  5046.9 2103.56
  5057.1 2105.21  5104.0 2104.79  5382.0 2104.81  5519.1 2108.91  5620.5 2115.44
  5708.7 2120.63  5800.3 2128.11  5820.6 2131.35  5912.3 2139.49  6024.3 2147.25
#Mann=8,-1,0
  3387.8    0.07       0  4766.1   0.035       0  4777.0    0.07       0
  4990.1    0.07       0  5026.4    0.07       0  5104.0    0.07       0
  5382.0    0.16       0  5620.5    0.07       0
Bank Sta=4990.1,5026.4
Exp/Cntr=0.3,0.1

Type RM Length L Ch R = 1,225000,500,500,500
BEGIN DESCRIPTION:
Sweetwater Creek 448.0
END DESCRIPTION:
XS GIS Cut Line= 5
      1382600.95      6844765.46      1382889.22      6843112.37
      1382855.29      6842896.05      1382753.63      6842731.54
      1382804.99      6842388.04
#Sta/Elev= 30
  3103.0 2120.77  3181.6 2119.28  3215.5 2120.98  3232.4 2118.00  3293.3 2117.81
  3374.5 2113.50  3443.6 2111.72  3476.0 2113.11  3503.2 2111.01  3587.7 2109.34
  3909.9 2111.21  4275.8 2110.50  4764.6 2109.59  4886.7 2110.30  4966.1 2104.86
  4977.8 2103.12  4996.5 2096.85  4996.6 2089.57  4997.2 2088.57  5025.0 2088.57
  5025.6 2089.57  5043.5 2094.49  5049.4 2101.01  5064.7 2103.07  5247.5 2102.41
  5371.0 2105.84  5399.2 2107.74  5436.9 2113.03  5487.6 2117.57  5540.7 2122.40
#Mann=7,-1,0
  3103.0    0.07       0  4275.8   0.035       0  4764.6    0.07       0
  4996.6    0.07       0  5025.6    0.07       0  5371.0    0.16       0
  5487.6    0.07       0
Bank Sta=4996.6,5025.6
Exp/Cntr=0.3,0.1

Type RM Length L Ch R = 1,224500,500,500,500
BEGIN DESCRIPTION:
Sweetwater Creek 447.0
END DESCRIPTION:
XS GIS Cut Line= 4
      1382956.47      6844691.47      1383162.97      6842708.56
      1383081.21      6842511.15      1382905.02      6842288.03
#Sta/Elev= 30
  2792.7 2121.34  2957.0 2118.98  2977.2 2120.60  2997.3 2117.74  3037.5 2117.49
  3102.3 2113.13  3178.2 2112.53  3218.5 2109.60  3266.2 2109.22  3624.6 2109.68
  4553.9 2108.65  4686.4 2107.14  4817.1 2101.94  4894.2 2101.23  4941.7 2102.30
  4970.9 2100.49  4982.1 2094.80  4988.8 2087.78  4989.3 2086.78  5010.1 2086.78
  5010.6 2087.78  5014.2 2096.18  5020.6 2101.56  5028.7 2099.76  5035.0 2100.60
  5063.9 2110.92  5107.9 2116.88  5220.6 2124.34  5256.3 2128.69  5284.3 2130.07
#Mann=9,-1,0
  2792.7    0.07       0  3102.3   0.035       0  3266.2    0.07       0
  3624.6   0.035       0  4553.9    0.07       0  4941.7    0.16       0
  4988.8    0.07       0  5010.6    0.16       0  5107.9    0.07       0
Bank Sta=4988.8,5010.6
Exp/Cntr=0.3,0.1