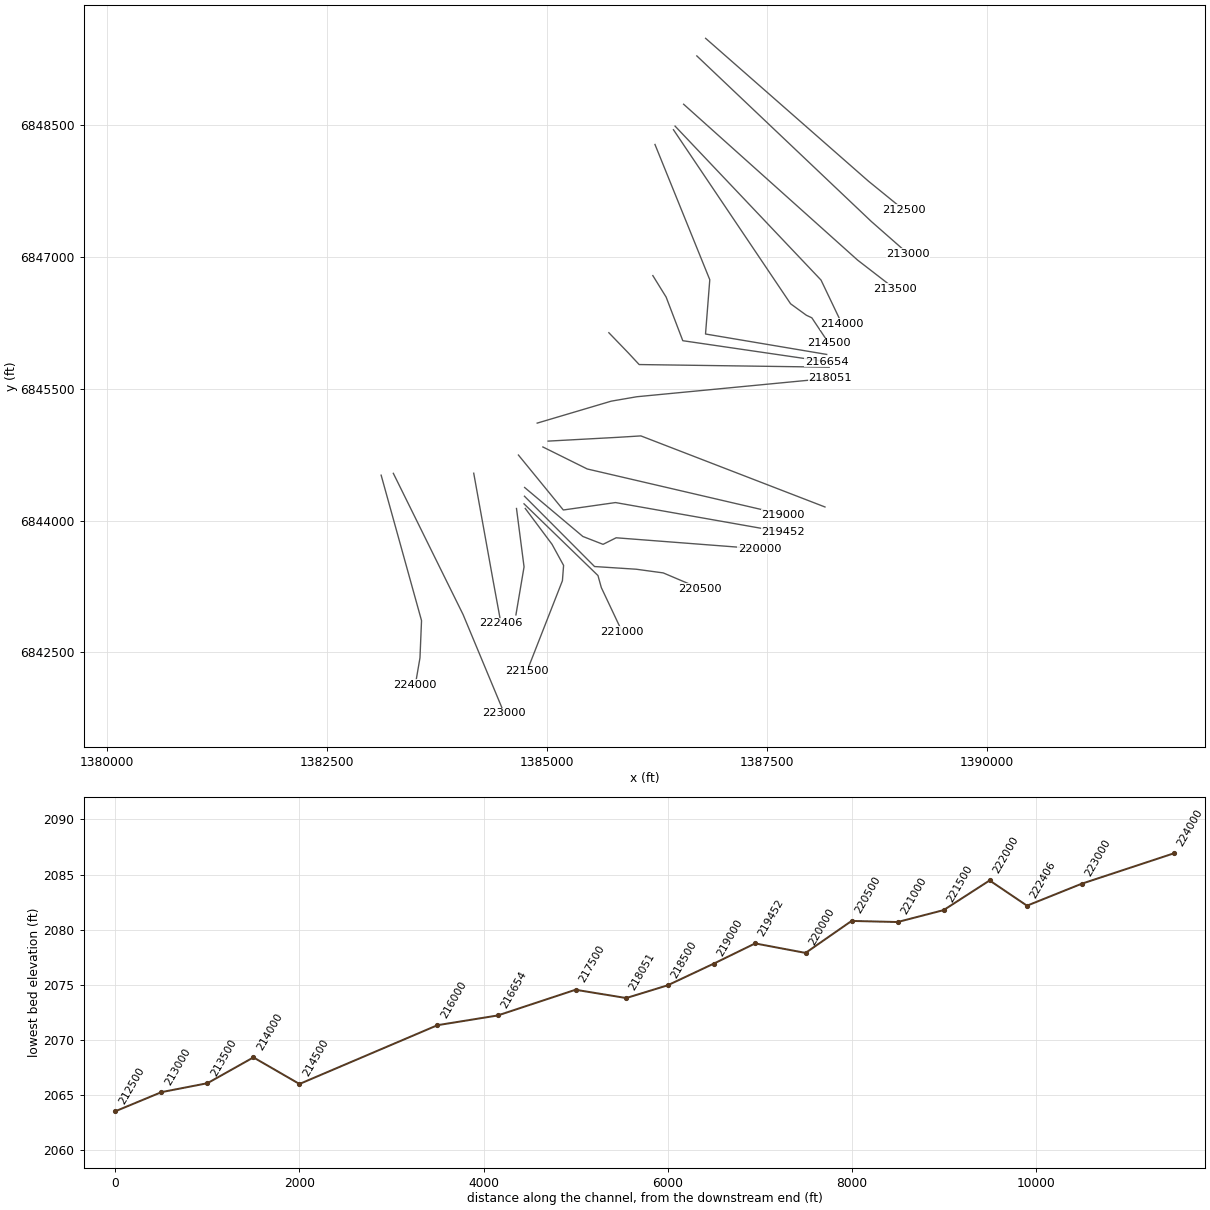
HEC-RAS study Sweetwater Creek.prj: Sweetwater Creek Base Level Engineering

--- Sweetwater Creek.g01 (geometry) --- (continued)

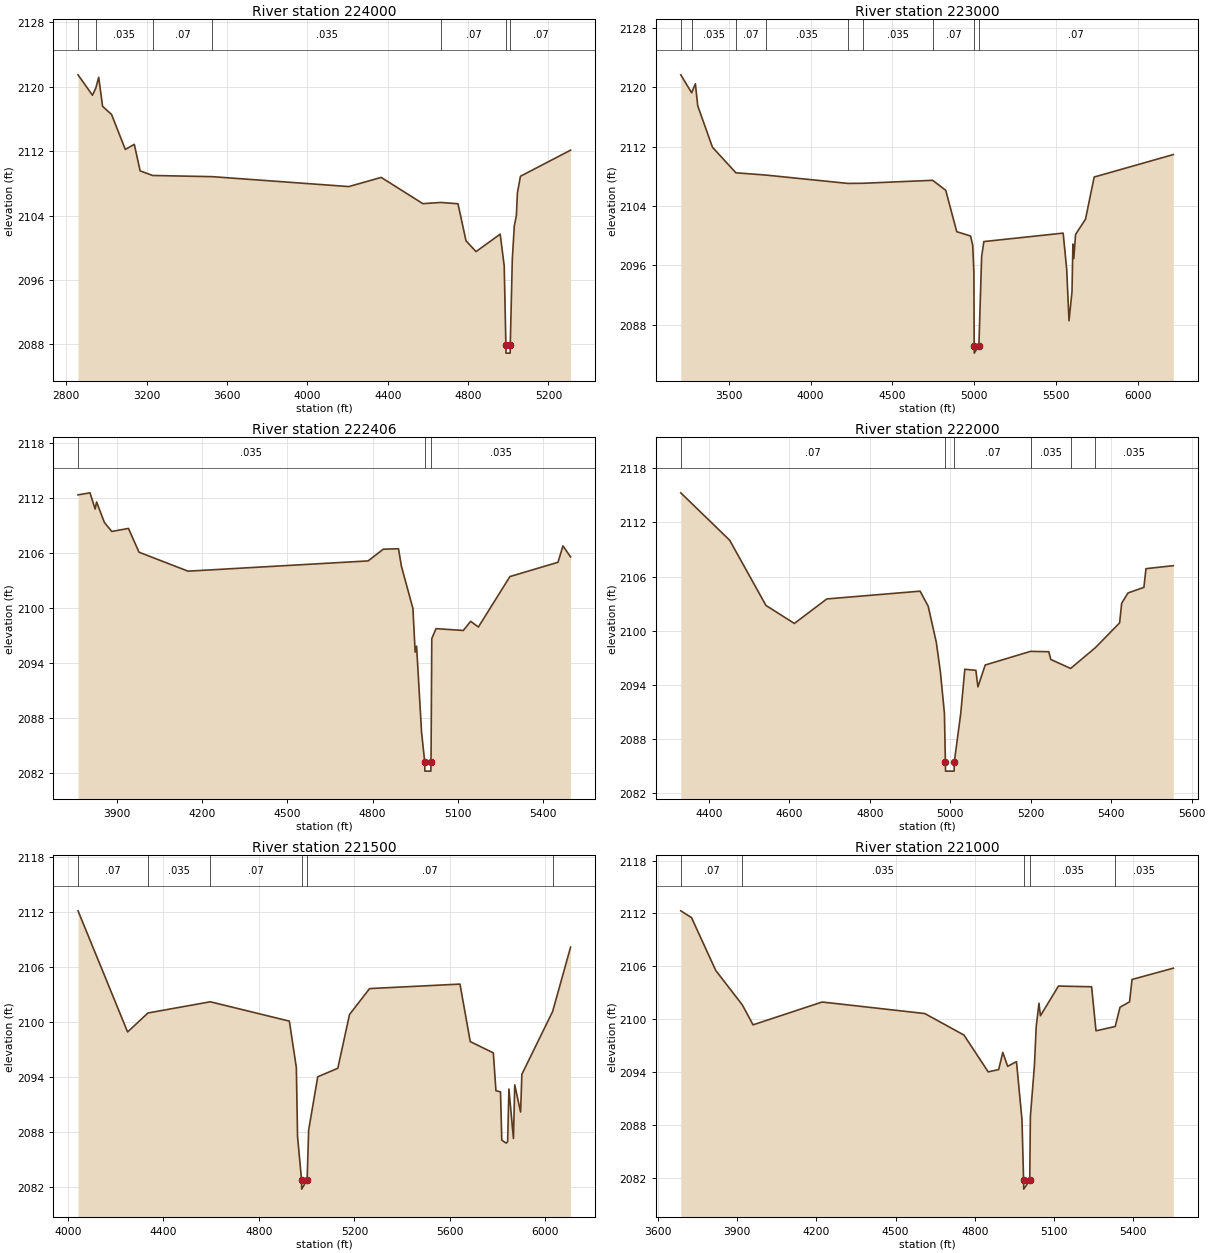
Type RM Length L Ch R = 1,224000,1000,1000,1000
BEGIN DESCRIPTION:
Sweetwater Creek 446.0
END DESCRIPTION:
XS GIS Cut Line= 4
      1383116.32      6844517.20      1383575.49      6842862.15
      1383557.75      6842437.99      1383505.19      6842131.97
#Sta/Elev= 30
  2857.9 2121.46  2929.7 2118.93  2946.3 2119.81  2960.8 2121.16  2980.1 2117.55
  3024.8 2116.54  3093.3 2112.20  3138.0 2112.83  3167.1 2109.54  3228.9 2108.97
  3527.4 2108.82  4206.2 2107.59  4367.5 2108.73  4575.0 2105.47  4664.3 2105.62
  4749.8 2105.46  4789.8 2100.86  4839.8 2099.52  4960.0 2101.69  4980.0 2097.74
  4988.4 2087.92  4988.8 2086.92  5009.7 2086.92  5010.1 2087.92  5020.3 2098.57
  5030.4 2102.74  5040.6 2104.00  5045.7 2106.81  5060.9 2108.87  5310.5 2112.11
#Mann=7,-1,0
  2857.9    0.07       0  2946.3   0.035       0  3228.9    0.07       0
  3527.4   0.035       0  4664.3    0.07       0  4988.4    0.07       0
  5010.1    0.07       0
Bank Sta=4988.4,5010.1
Exp/Cntr=0.3,0.1

Type RM Length L Ch R = 1,223000,594,594,594
BEGIN DESCRIPTION:
Sweetwater Creek 442.0
END DESCRIPTION:
XS GIS Cut Line= 3
      1383255.00      6844538.00      1384048.33      6842929.95
      1384515.87      6841806.55
#Sta/Elev= 30
  3206.9 2121.69  3273.4 2119.27  3296.1 2120.48  3310.7 2117.51  3400.5 2111.93
  3543.9 2108.48  3724.9 2108.18  4228.4 2107.05  4321.8 2107.07  4746.1 2107.47
  4826.1 2106.12  4893.5 2100.54  4977.7 2099.96  4991.0 2098.71  4998.3 2094.99
  4999.8 2085.17  5000.4 2084.17  5028.8 2085.17  5045.4 2097.17  5059.0 2099.21
  5543.7 2100.35  5565.3 2095.48  5579.3 2088.53  5597.7 2092.46  5603.1 2098.87
  5608.7 2096.93  5619.5 2100.18  5680.1 2102.22  5733.2 2107.91  6216.8 2110.94
#Mann=9,-1,0
  3206.9    0.07       0  3273.4   0.035       0  3543.9    0.07       0
  3724.9   0.035       0  4228.4    0.07       0  4321.8   0.035       0
  4746.1    0.07       0  4999.8    0.07       0  5028.8    0.07       0
Bank Sta=4999.8,5028.8
Exp/Cntr=0.3,0.1

Type RM Length L Ch R = 1,222406,406,406,406
BEGIN DESCRIPTION:
Sweetwater Creek 443.0
END DESCRIPTION:
XS GIS Cut Line= 3
      1384168.80      6844539.56      1384388.37      6843321.08
      1384478.44      6842831.50
#Sta/Elev= 30
  3761.9 2112.37  3804.1 2112.59  3822.2 2110.82  3827.3 2111.59  3854.9 2109.34
  3880.9 2108.37  3939.6 2108.70  3976.9 2106.10  4149.6 2104.03  4784.2 2105.15
  4837.7 2106.43  4891.3 2106.48  4901.5 2104.58  4942.2 2099.95  4950.0 2095.19
  4955.1 2095.83  4972.6 2086.43  4983.8 2083.18  4984.3 2082.18  5005.4 2082.18
  5005.9 2083.18  5008.6 2096.66  5023.5 2097.75  5119.8 2097.55  5145.5 2098.55
  5172.9 2097.93  5284.0 2103.44  5453.4 2105.00  5470.9 2106.79  5497.8 2105.59
#Mann=3,-1,0
  3761.9   0.035       0  4983.8   0.035       0  5005.9   0.035       0
Bank Sta=4983.8,5005.9
Exp/Cntr=0.3,0.1

Type RM Length L Ch R = 1,222000,500,500,500
BEGIN DESCRIPTION:
Sweetwater Creek 462.0
END DESCRIPTION:
XS GIS Cut Line= 3
      1384655.00      6844138.02      1384740.97      6843473.56
      1384648.48      6842926.93
#Sta/Elev= 30
  4330.0 2115.26  4451.5 2110.02  4541.8 2102.80  4612.4 2100.81  4693.0 2103.52
  4924.9 2104.38  4945.1 2102.71  4965.3 2098.71  4975.4 2095.45  4985.4 2090.87
  4987.8 2085.47  4988.2 2084.47  5009.5 2084.47  5009.9 2085.47  5025.9 2090.82
  5036.1 2095.74  5063.6 2095.62  5068.7 2093.79  5086.8 2096.21  5199.4 2097.72
  5244.8 2097.68  5249.9 2096.82  5299.2 2095.83  5360.9 2098.14  5420.9 2100.87
  5426.0 2103.04  5441.7 2104.18  5481.3 2104.80  5486.4 2106.87  5554.4 2107.20
#Mann=6,-1,0
  4330.0    0.07       0  4987.8    0.07       0  5009.9    0.07       0
  5199.4   0.035       0  5299.2    0.07       0  5360.9   0.035       0
Bank Sta=4987.8,5009.9
Exp/Cntr=0.3,0.1

Type RM Length L Ch R = 1,221500,500,500,500
BEGIN DESCRIPTION:
Sweetwater Creek 444.0
END DESCRIPTION:
XS GIS Cut Line= 5
      1384754.97      6844138.03      1385058.88      6843730.70
      1385190.40      6843490.24      1385177.03      6843315.84
      1384774.20      6842286.78
#Sta/Elev= 30
  4042.8 2112.13  4250.3 2098.92  4335.6 2100.99  4596.6 2102.21  4927.6 2100.10
  4956.9 2095.03  4961.9 2087.51  4978.7 2082.78  4979.1 2081.78  5002.0 2082.78
  5008.4 2088.22  5046.4 2094.03  5130.5 2094.96  5179.4 2100.82  5263.5 2103.65
  5642.0 2104.14  5685.0 2097.87  5781.6 2096.64  5792.6 2092.51  5811.7 2092.39
  5817.0 2087.12  5835.3 2086.80  5841.5 2086.95  5846.9 2092.70  5865.9 2087.30
  5871.3 2093.15  5895.8 2090.19  5901.1 2094.30  6029.9 2101.15  6105.1 2108.17
#Mann=6,-1,0
  4042.8    0.07       0  4335.6   0.035       0  4596.6    0.07       0
  4978.7    0.07       0  5002.0    0.07       0  6029.9   0.063       0
Bank Sta=4978.7,5002
Exp/Cntr=0.3,0.1

Type RM Length L Ch R = 1,221000,500,500,500
BEGIN DESCRIPTION:
Sweetwater Creek 441.0
END DESCRIPTION:
XS GIS Cut Line= 4
      1384740.40      6844190.98      1385581.18      6843374.99
      1385619.35      6843237.84      1385855.00      6842738.01
#Sta/Elev= 30
  3686.0 2112.29  3726.7 2111.52  3818.6 2105.52  3919.1 2101.62  3960.0 2099.35
  4221.9 2101.94  4610.8 2100.63  4759.2 2098.19  4851.1 2094.01  4890.7 2094.27
  4906.4 2096.22  4924.9 2094.64  4958.3 2095.17  4979.1 2088.58  4985.2 2081.70
  4985.7 2080.70  5008.5 2081.70  5010.9 2088.93  5026.2 2094.70  5033.0 2099.14
  5043.5 2101.80  5049.0 2100.38  5117.3 2103.75  5243.0 2103.67  5259.6 2098.67
  5332.4 2099.16  5350.7 2101.35  5386.8 2101.96  5396.2 2104.50  5552.6 2105.78
#Mann=5,-1,0
  3686.0    0.07       0  3919.1   0.035       0  4985.2    0.07       0
  5008.5   0.035       0  5332.4   0.035       0
Bank Sta=4985.2,5008.5
Exp/Cntr=0.3,0.1

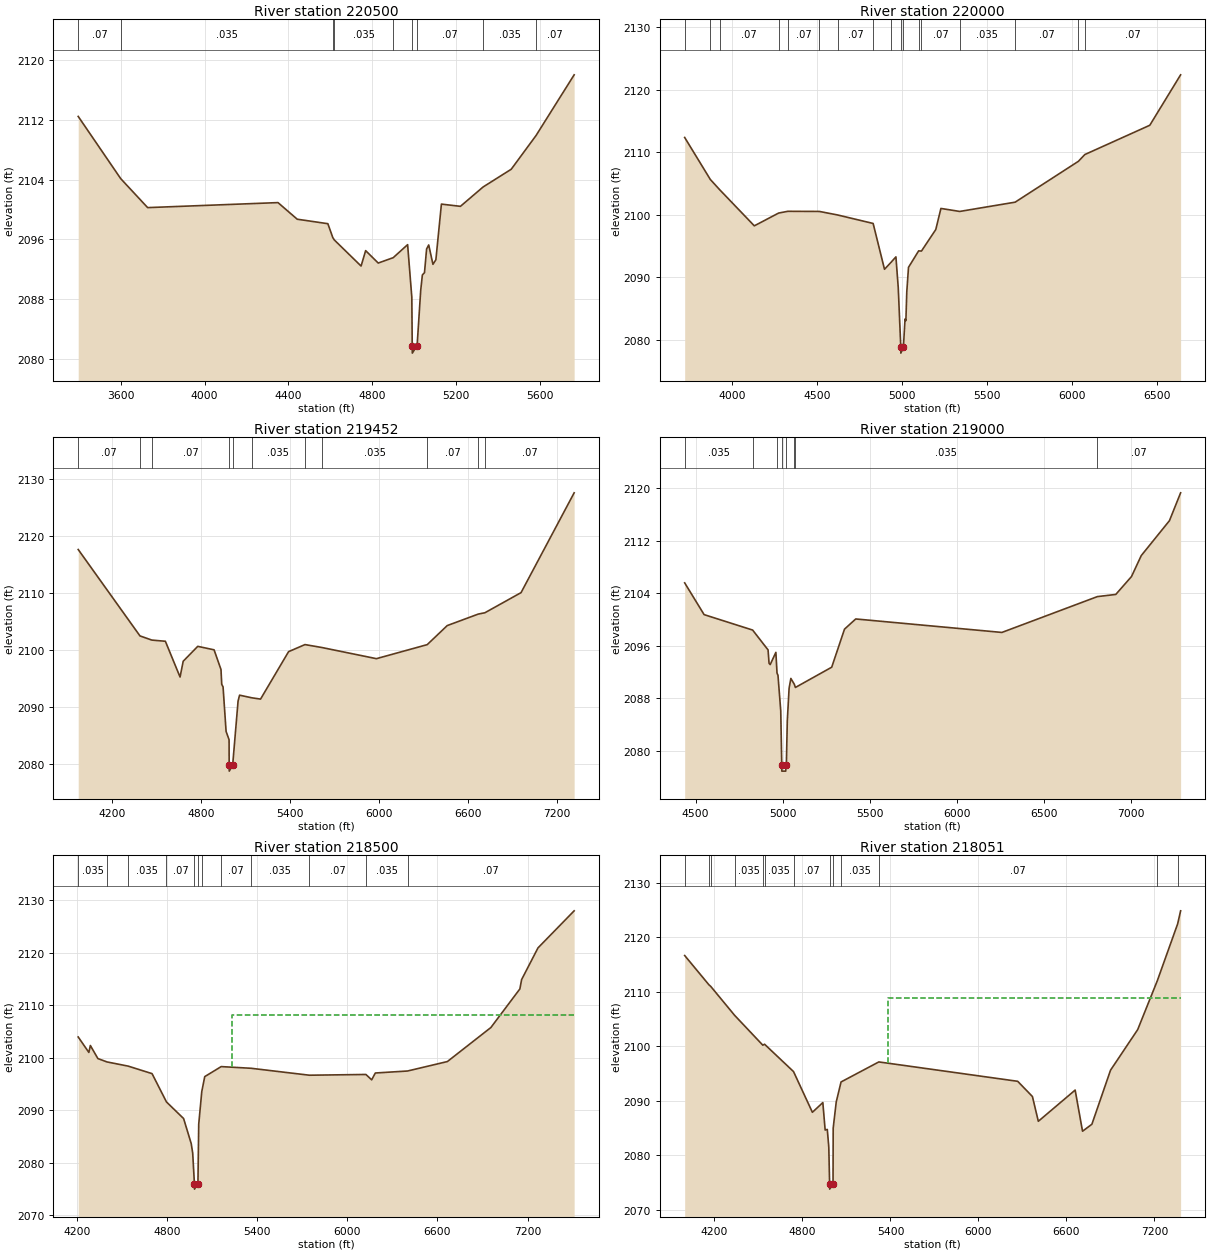
Type RM Length L Ch R = 1,220500,500,500,500
BEGIN DESCRIPTION:
Sweetwater Creek 440.0
END DESCRIPTION:
XS GIS Cut Line= 5
      1384745.67      6844277.43      1385542.27      6843477.48
      1386015.75      6843446.91      1386323.36      6843404.93
      1386740.97      6843227.52
#Sta/Elev= 30
  3396.6 2112.44  3599.6 2104.12  3728.1 2100.25  4350.3 2100.92  4442.2 2098.70
  4588.4 2098.10  4612.1 2096.24  4619.5 2095.92  4747.0 2092.44  4768.8 2094.50
  4828.9 2092.84  4900.5 2093.56  4969.2 2095.30  4989.2 2088.26  4991.2 2081.80
  4991.6 2080.80  5014.5 2081.80  5031.7 2089.20  5039.6 2091.25  5049.7 2091.55
  5059.8 2094.72  5069.9 2095.26  5090.1 2092.67  5104.1 2093.28  5130.5 2100.72
  5221.3 2100.42  5329.6 2103.01  5463.9 2105.38  5582.1 2109.88  5764.2 2118.00
#Mann=9,-1,0
  3396.6    0.07       0  3599.6   0.035       0  4612.1    0.07       0
  4619.5   0.035       0  4900.5    0.07       0  4991.2    0.07       0
  5014.5    0.07       0  5329.6   0.035       0  5582.1    0.07       0
Bank Sta=4991.2,5014.5
Exp/Cntr=0.3,0.1

Type RM Length L Ch R = 1,220000,548,548,548
BEGIN DESCRIPTION:
Sweetwater Creek 439.0
END DESCRIPTION:
XS GIS Cut Line= 5
      1384747.41      6844377.01      1385409.27      6843819.63
      1385638.92      6843730.13      1385787.85      6843804.66
      1387419.72      6843679.01
#Sta/Elev= 30
  3721.7 2112.36  3872.4 2105.65  3928.2 2103.99  4131.0 2098.24  4273.8 2100.28
  4327.5 2100.56  4513.5 2100.54  4620.1 2099.98  4829.4 2098.62  4896.2 2091.30
  4933.8 2092.39  4963.3 2093.28  4977.0 2088.37  4991.9 2078.90  4992.2 2077.90
  5007.4 2078.90  5016.9 2083.35  5021.9 2083.09  5027.2 2087.68  5037.3 2091.61
  5096.9 2094.24  5113.5 2094.21  5197.7 2097.65  5227.8 2101.02  5338.3 2100.54
  5664.1 2102.02  6035.9 2108.55  6073.6 2109.63  6455.5 2114.31  6636.7 2122.37
#Mann=17,-1,0
  3721.7    0.07       0  3872.4   0.035       0  3928.2    0.07       0
  4273.8   0.035       0  4327.5    0.07       0  4513.5   0.035       0
  4620.1    0.07       0  4829.4   0.035       0  4933.8    0.07       0
  4991.9    0.07       0  5007.4    0.07       0  5096.9   0.035       0
  5113.5    0.07       0  5338.3   0.035       0  5664.1    0.07       0
  6035.9   0.035       0  6073.6    0.07       0
Bank Sta=4991.9,5007.4
Exp/Cntr=0.3,0.1

Type RM Length L Ch R = 1,219452,452,452,452
BEGIN DESCRIPTION:
Sweetwater Creek 438.0
END DESCRIPTION:
XS GIS Cut Line= 4
      1384676.98      6844746.22      1385187.37      6844120.95
      1385780.46      6844205.43      1387687.46      6843868.15
#Sta/Elev= 30
  3972.5 2117.62  4388.8 2102.47  4468.5 2101.74  4560.0 2101.53  4659.0 2095.26
  4680.2 2098.03  4778.3 2100.64  4888.3 2100.03  4934.9 2096.57  4939.9 2093.99
  4948.9 2093.52  4969.2 2085.73  4989.4 2084.26  4990.0 2079.76  4990.5 2078.76
  5013.4 2079.76  5050.0 2091.04  5060.1 2092.08  5142.1 2091.62  5201.5 2091.39
  5390.5 2099.71  5501.1 2100.95  5614.0 2100.44  5982.5 2098.48  6324.9 2100.94
  6459.8 2104.28  6669.2 2106.30  6713.7 2106.53  6957.4 2110.06  7315.3 2127.56
#Mann=11,-1,0
  3972.5    0.07       0  4388.8   0.035       0  4468.5    0.07       0
  4990.0    0.07       0  5013.4    0.07       0  5142.1   0.035       0
  5501.1    0.07       0  5614.0   0.035       0  6324.9    0.07       0
  6669.2   0.035       0  6713.7    0.07       0
Bank Sta=4990,5013.4
Exp/Cntr=0.3,0.1

Type RM Length L Ch R = 1,219000,500,500,500
BEGIN DESCRIPTION:
Sweetwater Creek 437.0
END DESCRIPTION:
XS GIS Cut Line= 3
      1384955.00      6844838.00      1385459.20      6844587.72
      1387685.18      6844069.06
#Sta/Elev= 30
  4437.1 2105.56  4548.7 2100.73  4827.5 2098.38  4916.1 2095.36  4921.7 2093.33
  4928.3 2093.13  4960.9 2094.99  4967.5 2091.83  4973.0 2091.50  4988.9 2086.09
  4994.7 2077.92  4995.1 2076.92  5017.5 2076.92  5018.0 2077.92  5021.1 2077.92
  5026.5 2084.55  5036.8 2089.51  5047.0 2091.02  5066.7 2090.14  5073.1 2089.65
  5281.6 2092.73  5355.1 2098.52  5419.6 2100.07  6259.2 2098.02  6807.4 2103.47
  6913.2 2103.80  7003.4 2106.52  7059.5 2109.71  7221.4 2115.02  7285.6 2119.26
#Mann=8,-1,0
  4437.1   0.035       0  4827.5    0.07       0  4967.5   0.035       0
  4994.7   0.035       0  5018.0   0.035       0  5066.7    0.07       0
  5073.1   0.035       0  6807.4    0.07       0
Bank Sta=4994.7,5018
Exp/Cntr=0.3,0.1

Type RM Length L Ch R = 1,218500,449,449,449
BEGIN DESCRIPTION:
Sweetwater Creek 436.0
END DESCRIPTION:
XS GIS Cut Line= 4
      1385014.33      6844904.68      1385803.77      6844947.60
      1386069.25      6844963.94      1388161.83      6844155.23
#Sta/Elev= 30
  4209.4 2103.93  4280.2 2100.99  4290.2 2102.31  4340.3 2099.82  4400.7 2099.18
  4542.0 2098.38  4700.8 2096.95  4796.7 2091.56  4910.7 2088.40  4961.2 2083.65
  4971.2 2081.84  4982.7 2075.96  4983.2 2074.96  5006.0 2075.96  5011.3 2087.33
  5031.7 2093.55  5051.3 2096.38  5160.9 2098.29  5359.5 2097.97  5747.4 2096.65
  6123.8 2096.79  6162.0 2095.77  6186.4 2097.07  6400.7 2097.45  6665.9 2099.25
  6955.3 2105.73  7148.3 2113.08  7159.7 2114.85  7268.7 2120.89  7509.4 2127.95
#Mann=12,-1,0
  4209.4   0.035       0  4400.7    0.07       0  4542.0   0.035       0
  4796.7    0.07       0  4982.7    0.07       0  5006.0    0.07       0
  5031.7   0.035       0  5160.9    0.07       0  5359.5   0.035       0
  5747.4    0.07       0  6123.8   0.035       0  6400.7    0.07       0
#XS Ineff=2,0
       0                 5234.50    0.00 2108.02
Permanent Ineff=
       F       F
Bank Sta=4982.7,5006
Exp/Cntr=0.3,0.1

Type RM Length L Ch R = 1,218051,551,551,551
BEGIN DESCRIPTION:
Sweetwater Creek 435.0
END DESCRIPTION:
XS GIS Cut Line= 4
      1384890.32      6845109.52      1385731.85      6845359.30
      1386023.72      6845409.72      1388220.67      6845621.06
#Sta/Elev= 30
  3997.2 2116.62  4162.4 2111.26  4174.9 2110.96  4338.0 2105.65  4529.9 2100.19
  4541.9 2100.36  4739.3 2095.35  4867.9 2087.89  4939.1 2089.67  4954.9 2084.64
  4969.5 2084.75  4979.7 2081.52  4985.3 2074.81  4985.8 2073.81  5008.6 2074.81
  5009.7 2084.99  5030.4 2089.78  5063.3 2093.45  5320.9 2097.12  6267.5 2093.57
  6368.0 2090.78  6408.2 2086.24  6659.3 2091.96  6709.6 2084.42  6773.4 2085.70
  6900.4 2095.60  7085.8 2103.05  7219.6 2112.01  7358.2 2122.43  7378.3 2124.81
#Mann=13,-1,0
  3997.2    0.07       0  4162.4   0.035       0  4174.9    0.07       0
  4338.0   0.035       0  4529.9    0.07       0  4541.9   0.035       0
  4739.3    0.07       0  4985.3    0.07       0  5008.6    0.07       0
  5063.3   0.035       0  5320.9    0.07       0  7219.6   0.035       0
  7358.2    0.07       0
#XS Ineff=2,0
       0                 5384.30    0.00 2108.85
Permanent Ineff=
       F       F
Bank Sta=4985.3,5008.6
Exp/Cntr=0.3,0.1

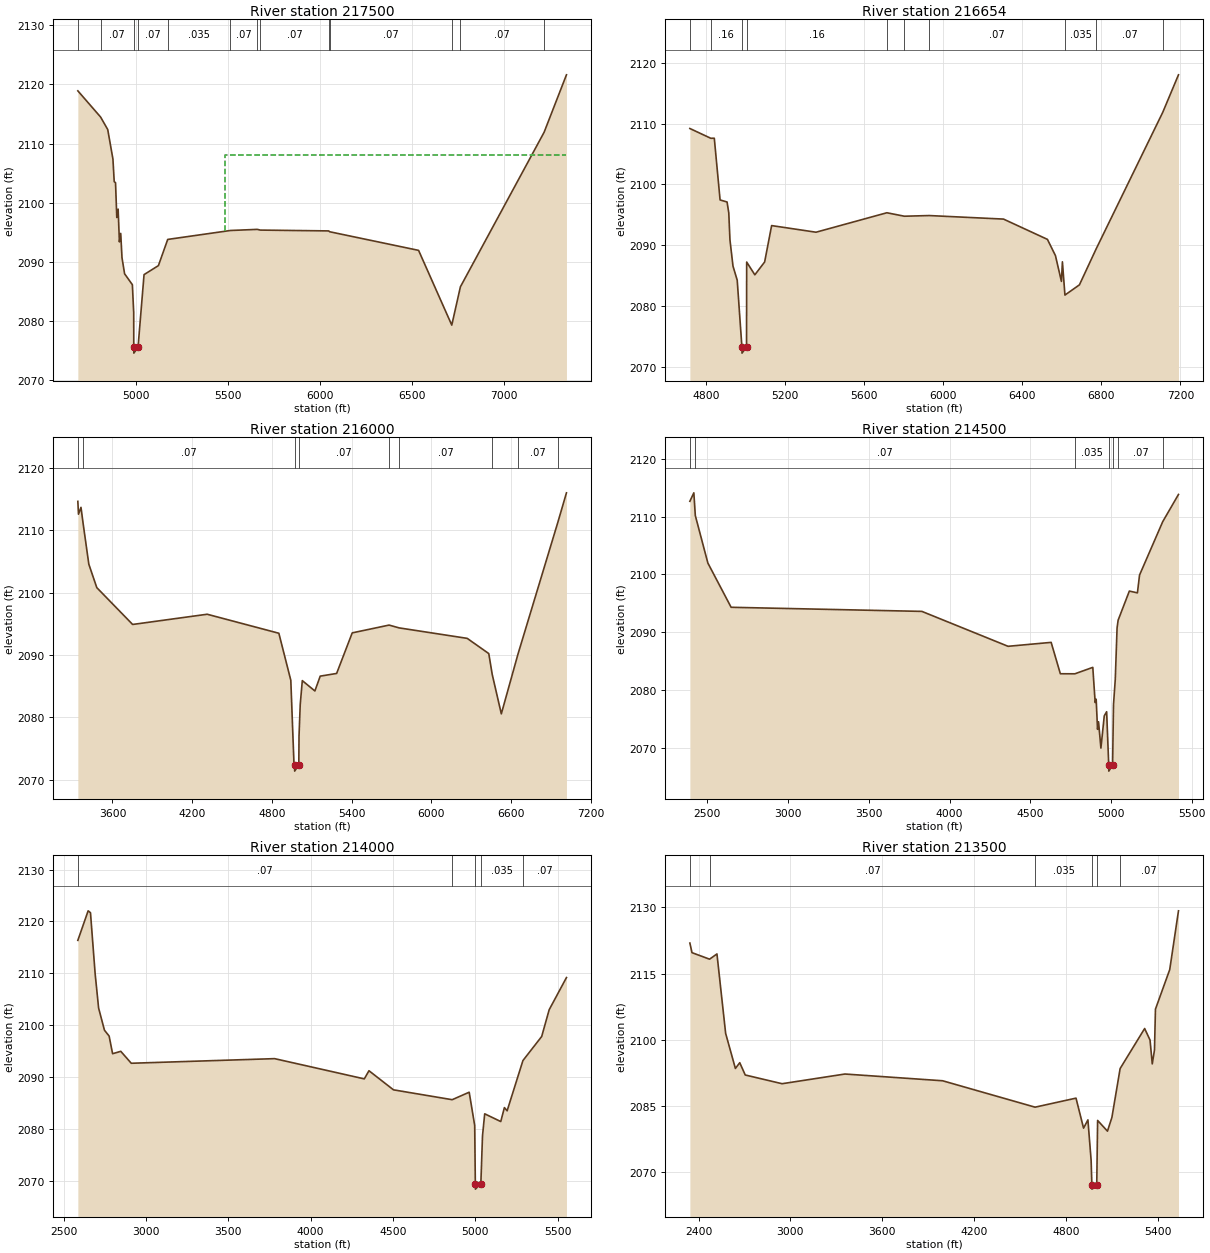
Type RM Length L Ch R = 1,217500,846,846,846
BEGIN DESCRIPTION:
Sweetwater Creek 434.0
END DESCRIPTION:
XS GIS Cut Line= 4
      1385704.97      6846138.03      1385925.86      6845908.84
      1386049.43      6845775.94      1388210.15      6845745.99
#Sta/Elev= 30
  4681.7 2118.92  4805.6 2114.49  4844.5 2112.37  4872.8 2107.37  4879.7 2103.56
  4886.9 2103.38  4893.8 2097.50  4901.1 2098.92  4908.0 2093.37  4915.2 2094.81
  4922.1 2090.70  4936.3 2087.98  4978.7 2086.13  4985.9 2081.36  4986.2 2075.56
  4986.7 2074.56  5009.5 2075.56  5042.2 2087.84  5120.4 2089.36  5171.1 2093.79
  5512.0 2095.30  5658.7 2095.49  5675.3 2095.37  6047.7 2095.23  6052.8 2095.09
  6537.2 2091.94  6717.9 2079.30  6765.0 2085.78  7220.8 2111.92  7342.4 2121.63
#Mann=13,-1,0
  4681.7   0.035       0  4805.6    0.07       0  4986.2    0.07       0
  5009.5    0.07       0  5171.1   0.035       0  5512.0    0.07       0
  5658.7   0.035       0  5675.3    0.07       0  6047.7   0.035       0
  6052.8    0.07       0  6717.9   0.035       0  6765.0    0.07       0
  7220.8   0.035       0
#XS Ineff=2,0
    0.00 4520.10 2108.13 5480.70    0.00 2108.13
Permanent Ineff=
       F       F
Bank Sta=4986.2,5009.5
Exp/Cntr=0.3,0.1

Type RM Length L Ch R = 1,216654,654,654,654
BEGIN DESCRIPTION:
Sweetwater Creek 432.0
END DESCRIPTION:
XS GIS Cut Line= 4
      1386205.00      6846788.00      1386356.06      6846543.62
      1386545.39      6846047.31      1388180.77      6845807.97
#Sta/Elev= 30
  4719.0 2109.18  4824.9 2107.57  4842.5 2107.58  4871.8 2097.43  4907.1 2097.09
  4915.8 2095.29  4921.7 2090.86  4937.1 2086.54  4958.4 2084.23  4982.2 2073.23
  4982.7 2072.23  5005.6 2073.23  5006.3 2087.21  5047.6 2085.11  5097.1 2087.22
  5132.5 2093.21  5357.1 2092.12  5715.4 2095.32  5803.9 2094.75  5929.8 2094.86
  6305.2 2094.28  6527.5 2090.94  6568.0 2088.27  6598.2 2084.03  6603.2 2087.25
  6616.0 2081.78  6689.2 2083.46  6774.1 2089.39  7110.4 2111.82  7190.3 2118.01
#Mann=10,-1,0
  4719.0    0.07       0  4824.9    0.16       0  4982.2    0.07       0
  5005.6    0.16       0  5715.4    0.07       0  5803.9   0.035       0
  5929.8    0.07       0  6616.0   0.035       0  6774.1    0.07       0
  7110.4   0.035       0
Bank Sta=4982.2,5005.6
Exp/Cntr=0.3,0.1

Type RM Length L Ch R = 1,216000,1500,1500,1500
BEGIN DESCRIPTION:
Sweetwater Creek 431.0
END DESCRIPTION:
XS GIS Cut Line= 4
      1386229.28      6848280.21      1386852.29      6846741.13
      1386803.86      6846123.47      1388181.46      6845891.21
#Sta/Elev= 30
  3339.6 2114.63  3344.4 2112.57  3363.2 2113.67  3380.8 2110.85  3422.2 2104.55
  3482.2 2100.79  3751.9 2094.88  4312.9 2096.52  4852.3 2093.47  4942.3 2085.92
  4966.4 2072.35  4970.7 2072.35  4971.3 2071.35  5002.4 2072.35  5004.1 2077.01
  5013.2 2082.06  5028.8 2085.87  5123.5 2084.21  5163.6 2086.59  5287.1 2087.02
  5404.4 2093.53  5681.7 2094.78  5757.4 2094.33  6269.7 2092.65  6432.0 2090.21
  6458.1 2086.85  6526.5 2080.54  6651.9 2090.13  6951.0 2111.21  7016.6 2116.00
#Mann=9,-1,0
  3339.6   0.035       0  3380.8    0.07       0  4970.7    0.07       0
  5002.4    0.07       0  5681.7   0.035       0  5757.4    0.07       0
  6458.1   0.035       0  6651.9    0.07       0  6951.0   0.035       0
Bank Sta=4970.7,5002.4
Exp/Cntr=0.3,0.1

Type RM Length L Ch R = 1,214500,500,500,500
BEGIN DESCRIPTION:
Sweetwater Creek 428.0
END DESCRIPTION:
XS GIS Cut Line= 5
      1386439.32      6848447.88      1387771.11      6846467.21
      1387950.60      6846336.70      1388012.42      6846307.86
      1388206.33      6846016.16
#Sta/Elev= 30
  2391.3 2112.63  2415.9 2114.09  2425.0 2110.16  2502.8 2101.96  2646.8 2094.32
  3828.7 2093.61  4362.6 2087.58  4629.6 2088.26  4686.6 2082.84  4776.4 2082.83
  4887.6 2083.94  4902.3 2077.87  4908.5 2078.44  4917.0 2073.24  4923.2 2074.55
  4937.9 2070.00  4958.7 2075.57  4973.4 2076.28  4986.4 2067.02  4986.8 2066.02
  5010.2 2067.02  5015.9 2077.49  5026.9 2081.88  5038.0 2090.75  5044.6 2092.09
  5114.1 2097.12  5164.1 2096.81  5177.2 2099.88  5320.9 2109.11  5418.5 2113.81
#Mann=7,-1,0
  2391.3   0.035       0  2425.0    0.07       0  4776.4   0.035       0
  4986.4   0.035       0  5010.2   0.035       0  5044.6    0.07       0
  5320.9   0.035       0
Bank Sta=4986.4,5010.2
Exp/Cntr=0.3,0.1

Type RM Length L Ch R = 1,214000,500,500,500
BEGIN DESCRIPTION:
Sweetwater Creek 427.0
END DESCRIPTION:
XS GIS Cut Line= 3
      1386457.68      6848489.10      1388117.01      6846737.05
      1388355.00      6846237.99
#Sta/Elev= 30
  2586.9 2116.36  2649.4 2122.05  2663.6 2121.69  2691.9 2109.93  2712.9 2103.32
  2748.5 2099.05  2776.8 2097.92  2797.9 2094.52  2847.6 2094.98  2911.1 2092.68
  3781.3 2093.57  4325.8 2089.67  4354.1 2091.24  4502.9 2087.56  4859.2 2085.66
  4962.5 2087.10  4995.9 2080.70  4999.8 2069.43  5000.4 2068.43  5031.5 2069.43
  5034.0 2070.17  5043.3 2078.70  5056.6 2082.94  5154.1 2081.45  5176.2 2084.14
  5192.8 2083.52  5288.7 2093.20  5402.6 2097.84  5448.0 2102.99  5552.9 2109.19
#Mann=5,-1,0
  2586.9    0.07       0  4859.2   0.035       0  4999.8   0.035       0
  5031.5   0.035       0  5288.7    0.07       0
Bank Sta=4999.8,5031.5
Exp/Cntr=0.3,0.1

Type RM Length L Ch R = 1,213500,500,500,500
BEGIN DESCRIPTION:
Sweetwater Creek 426.0
END DESCRIPTION:
XS GIS Cut Line= 3
      1386554.98      6848738.02      1388532.60      6846964.48
      1388955.03      6846637.98
#Sta/Elev= 30
  2343.6 2121.91  2357.4 2119.73  2472.2 2118.25  2520.4 2119.44  2577.2 2101.41
  2640.8 2093.46  2669.2 2094.77  2705.1 2091.98  2945.8 2090.00  3356.2 2092.20
  3993.9 2090.67  4597.6 2084.68  4864.8 2086.73  4914.1 2079.92  4942.5 2081.80
  4963.5 2072.61  4968.3 2067.09  4968.9 2066.09  5000.2 2067.09  5005.9 2081.67
  5070.2 2079.24  5099.2 2082.36  5152.9 2093.44  5312.9 2102.52  5348.2 2099.90
  5362.7 2094.50  5377.2 2097.64  5383.5 2106.91  5476.8 2115.89  5533.9 2129.22
#Mann=6,-1,0
  2343.6   0.035       0  2472.2    0.07       0  4597.6   0.035       0
  4968.3   0.035       0  5000.2   0.035       0  5152.9    0.07       0
Bank Sta=4968.3,5000.2
Exp/Cntr=0.3,0.1

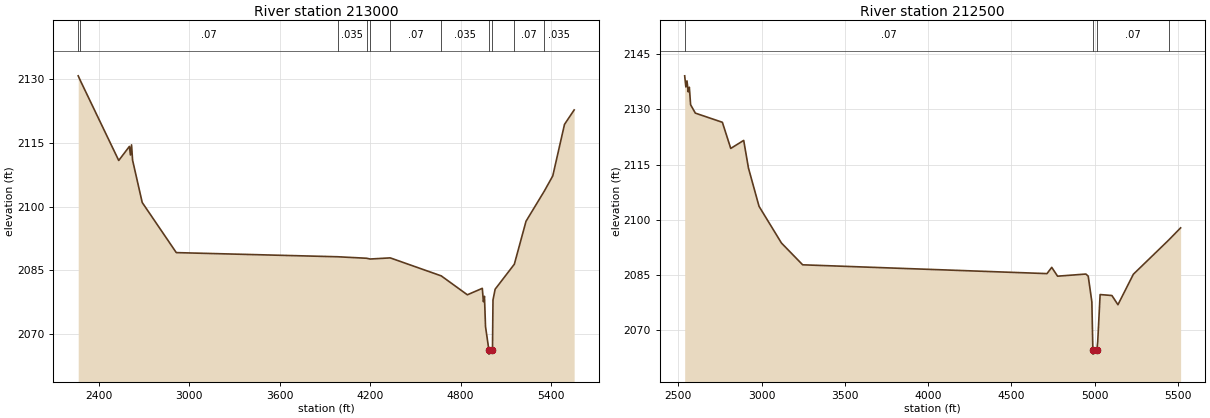
Type RM Length L Ch R = 1,213000,500,500,500
BEGIN DESCRIPTION:
Sweetwater Creek 425.0
END DESCRIPTION:
XS GIS Cut Line= 3
      1386704.97      6849288.03      1388689.00      6847403.64
      1389104.96      6847038.03
#Sta/Elev= 30
  2263.7 2130.80  2278.8 2129.61  2532.5 2110.87  2603.3 2114.18  2610.2 2112.16
  2617.5 2114.55  2624.4 2110.94  2688.3 2100.98  2914.4 2089.18  3986.4 2088.20
  4177.6 2087.85  4200.2 2087.67  4333.5 2087.94  4672.2 2083.70  4845.4 2079.25
  4944.5 2080.77  4951.8 2077.62  4958.7 2078.89  4965.9 2071.73  4988.1 2066.28
  4988.5 2065.28  5012.0 2066.28  5015.4 2078.04  5029.6 2080.56  5157.0 2086.45
  5234.6 2096.57  5355.6 2103.65  5412.0 2107.24  5489.8 2119.37  5553.8 2122.77
#Mann=11,-1,0
  2263.7   0.035       0  2278.8    0.07       0  3986.4   0.035       0
  4177.6    0.07       0  4200.2   0.035       0  4333.5    0.07       0
  4672.2   0.035       0  4988.1   0.035       0  5012.0   0.035       0
  5157.0    0.07       0  5355.6   0.035       0
Bank Sta=4988.1,5012
Exp/Cntr=0.3,0.1

Type RM Length L Ch R = 1,212500,500,500,500
BEGIN DESCRIPTION:
Sweetwater Creek 424.0
END DESCRIPTION:
XS GIS Cut Line= 3
      1386805.00      6849488.00      1388654.74      6847863.68
      1389054.98      6847538.01
#Sta/Elev= 30
  2538.3 2139.14  2545.4 2136.12  2552.1 2137.77  2559.7 2134.78  2566.3 2136.04
  2573.9 2131.29  2602.3 2129.01  2764.6 2126.52  2814.9 2119.42  2892.7 2121.60
  2921.2 2114.10  2984.8 2103.69  3119.5 2093.72  3246.7 2087.81  4713.7 2085.42
  4742.1 2087.12  4777.2 2084.72  4947.1 2085.30  4961.3 2084.72  4983.1 2077.75
  4989.2 2064.55  4989.7 2063.55  5013.1 2064.55  5018.3 2066.98  5032.7 2079.73
  5103.5 2079.47  5139.7 2076.97  5232.3 2085.25  5444.6 2094.54  5516.0 2097.85
#Mann=4,-1,0
  2538.3    0.07       0  4989.2    0.07       0  5013.1    0.07       0
  5444.6    0.07       0
Bank Sta=4989.2,5013.1
Exp/Cntr=0.3,0.1