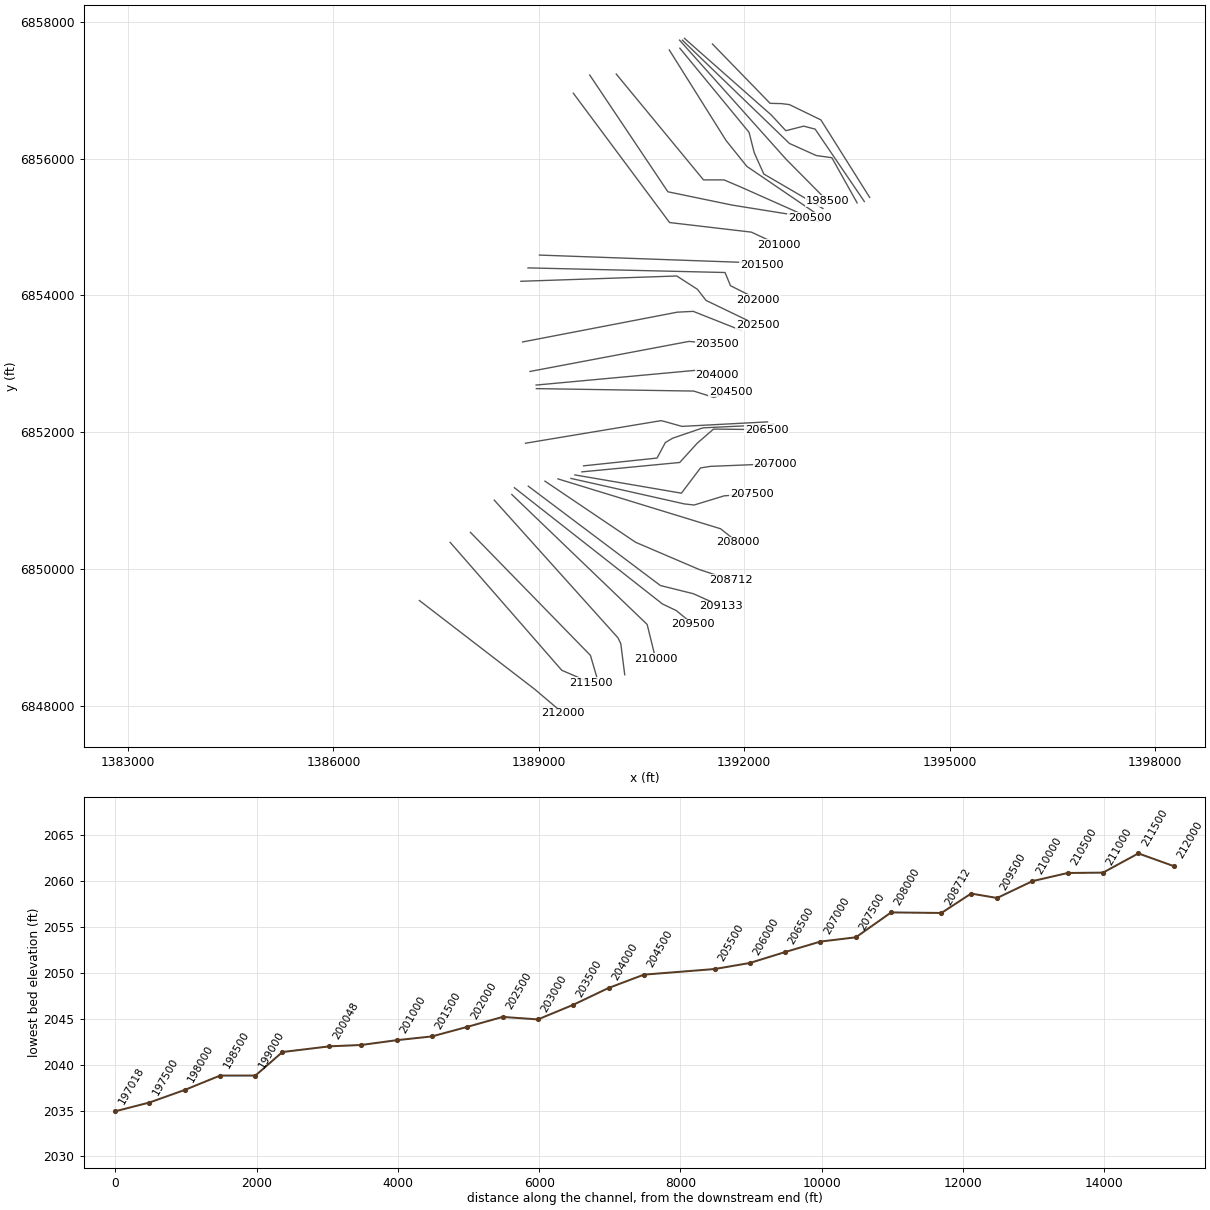
HEC-RAS study Sweetwater Creek.prj: Sweetwater Creek Base Level Engineering

--- Sweetwater Creek.g01 (geometry) --- (continued)

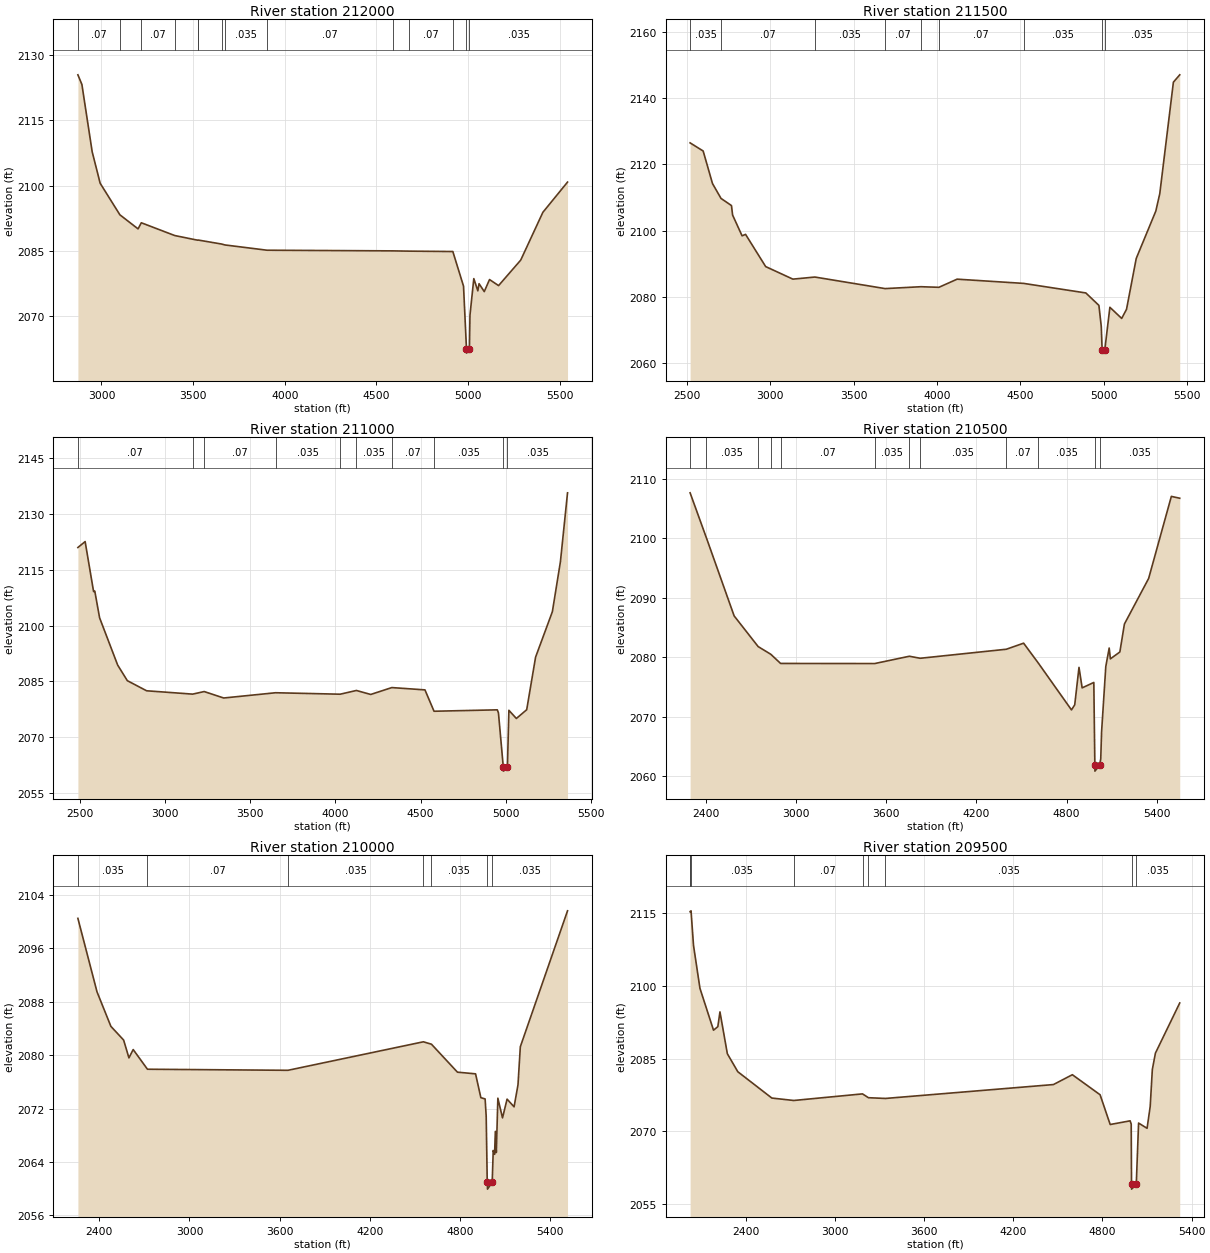
Type RM Length L Ch R = 1,212000,500,500,500
BEGIN DESCRIPTION:
Sweetwater Creek 423.0
END DESCRIPTION:
XS GIS Cut Line= 3
      1387254.97      6849538.03      1388941.46      6848239.14
      1389354.99      6847888.01
#Sta/Elev= 30
  2871.3 2125.47  2893.1 2123.27  2949.2 2107.81  2992.8 2100.58  3100.4 2093.34
  3199.5 2090.11  3217.3 2091.51  3399.6 2088.58  3524.8 2087.51  3527.4 2087.55
  3655.1 2086.63  3673.5 2086.42  3903.3 2085.21  4589.9 2085.06  4678.8 2085.00
  4916.8 2084.91  4975.1 2076.97  4991.2 2062.59  4991.5 2061.59  5007.2 2062.59
  5010.3 2070.32  5031.2 2078.69  5053.2 2075.89  5059.8 2077.53  5088.3 2075.71
  5116.9 2078.48  5166.3 2077.09  5287.1 2082.94  5408.0 2093.91  5542.5 2100.85
#Mann=14,-1,0
  2871.3    0.07       0  3100.4   0.035       0  3217.3    0.07       0
  3399.6   0.035       0  3524.8    0.07       0  3527.4   0.035       0
  3655.1    0.07       0  3673.5   0.035       0  3903.3    0.07       0
  4589.9   0.035       0  4678.8    0.07       0  4916.8   0.035       0
  4991.2   0.035       0  5007.2   0.035       0
Bank Sta=4991.2,5007.2
Exp/Cntr=0.3,0.1

Type RM Length L Ch R = 1,211500,500,500,500
BEGIN DESCRIPTION:
Sweetwater Creek 422.0
END DESCRIPTION:
XS GIS Cut Line= 3
      1387705.03      6850387.97      1389334.79      6848517.74
      1389754.97      6848338.01
#Sta/Elev= 30
  2519.3 2126.48  2597.6 2124.02  2653.6 2114.19  2704.7 2109.70  2767.5 2107.54
  2774.2 2104.68  2831.1 2098.40  2852.0 2098.84  2972.6 2089.11  3135.9 2085.32
  3267.9 2085.95  3689.2 2082.46  3904.3 2083.03  4012.1 2082.85  4121.3 2085.31
  4520.7 2084.03  4893.5 2081.15  4972.0 2077.39  4986.2 2070.99  4991.3 2063.97
  4991.6 2062.97  5007.3 2063.97  5037.9 2076.82  5108.7 2073.45  5137.7 2076.21
  5196.0 2091.57  5313.7 2105.91  5337.3 2111.16  5418.9 2144.81  5457.0 2147.03
#Mann=9,-1,0
  2519.3   0.035       0  2704.7    0.07       0  3267.9   0.035       0
  3689.2    0.07       0  3904.3   0.035       0  4012.1    0.07       0
  4520.7   0.035       0  4991.3   0.035       0  5007.3   0.035       0
Bank Sta=4991.3,5007.3
Exp/Cntr=0.3,0.1

Type RM Length L Ch R = 1,211000,500,500,500
BEGIN DESCRIPTION:
Sweetwater Creek 421.0
END DESCRIPTION:
XS GIS Cut Line= 3
      1388000.92      6850534.06      1389753.46      6848736.08
      1389855.00      6848387.99
#Sta/Elev= 30
  2489.2 2120.97  2531.7 2122.56  2581.3 2109.12  2588.3 2109.26  2616.6 2102.07
  2722.6 2089.38  2779.2 2085.19  2892.3 2082.47  3162.5 2081.57  3230.4 2082.26
  3345.0 2080.53  3649.3 2081.94  4028.5 2081.55  4123.6 2082.55  4207.7 2081.48
  4331.4 2083.33  4525.9 2082.71  4579.2 2076.97  4950.3 2077.35  4957.2 2076.54
  4985.8 2061.88  4986.3 2060.88  5009.8 2061.88  5018.5 2077.22  5062.4 2075.03
  5123.0 2077.38  5175.1 2091.50  5273.7 2103.73  5320.9 2117.16  5362.6 2135.66
#Mann=10,-1,0
  2489.2    0.07       0  3162.5   0.035       0  3230.4    0.07       0
  3649.3   0.035       0  4028.5    0.07       0  4123.6   0.035       0
  4331.4    0.07       0  4579.2   0.035       0  4985.8   0.035       0
  5009.8   0.035       0
Bank Sta=4985.8,5009.8
Exp/Cntr=0.3,0.1

Type RM Length L Ch R = 1,210500,500,500,500
BEGIN DESCRIPTION:
Sweetwater Creek 420.0
END DESCRIPTION:
XS GIS Cut Line= 4
      1388348.54      6851005.74      1390155.66      6848992.68
      1390196.89      6848907.73      1390254.21      6848452.65
#Sta/Elev= 30
  2294.8 2107.67  2403.0 2100.11  2587.8 2086.96  2747.5 2081.80  2831.9 2080.50
  2896.9 2078.96  3522.9 2078.94  3753.8 2080.17  3826.1 2079.83  4399.2 2081.35
  4514.1 2082.37  4612.9 2078.99  4832.6 2071.14  4854.3 2072.00  4882.7 2078.30
  4903.6 2074.85  4981.3 2075.76  4988.2 2061.84  4988.8 2060.84  5020.1 2061.84
  5027.4 2062.90  5032.9 2067.42  5061.0 2078.44  5083.6 2081.55  5091.5 2079.73
  5154.6 2080.89  5184.9 2085.59  5346.1 2093.26  5497.3 2107.07  5553.1 2106.76
#Mann=12,-1,0
  2294.8    0.07       0  2403.0   0.035       0  2747.5    0.07       0
  2831.9   0.035       0  2896.9    0.07       0  3522.9   0.035       0
  3753.8    0.07       0  3826.1   0.035       0  4399.2    0.07       0
  4612.9   0.035       0  4988.2   0.035       0  5020.1   0.035       0
Bank Sta=4988.2,5020.1
Exp/Cntr=0.3,0.1

Type RM Length L Ch R = 1,210000,500,500,500
BEGIN DESCRIPTION:
Sweetwater Creek 419.0
END DESCRIPTION:
XS GIS Cut Line= 3
      1388605.00      6851088.00      1390581.96      6849188.09
      1390705.00      6848688.01
#Sta/Elev= 30
  2258.1 2100.51  2385.3 2089.50  2477.4 2084.34  2562.3 2082.28  2597.6 2079.61
  2625.9 2080.86  2720.8 2077.91  3655.3 2077.75  4556.1 2082.02  4609.8 2081.66
  4782.8 2077.47  4903.3 2077.22  4938.5 2073.65  4966.8 2073.46  4974.0 2070.85
  4980.9 2061.05  4982.0 2060.95  4982.6 2059.95  5014.0 2060.95  5020.7 2065.74
  5029.7 2065.16  5034.9 2068.60  5041.3 2065.43  5051.6 2073.57  5082.5 2070.62
  5112.8 2073.43  5159.5 2072.28  5185.5 2075.58  5201.0 2081.28  5515.0 2101.64
#Mann=7,-1,0
  2258.1   0.035       0  2720.8    0.07       0  3655.3   0.035       0
  4556.1    0.07       0  4609.8   0.035       0  4982.0   0.035       0
  5014.0   0.035       0
Bank Sta=4982,5014
Exp/Cntr=0.3,0.1

Type RM Length L Ch R = 1,209500,367,367,367
BEGIN DESCRIPTION:
Sweetwater Creek 418.0
END DESCRIPTION:
XS GIS Cut Line= 4
      1388642.51      6851187.51      1390805.00      6849488.00
      1391007.53      6849390.91      1391254.98      6849188.01
#Sta/Elev= 30
  2025.0 2115.26  2025.3 2115.26  2031.3 2115.45  2047.9 2108.32  2091.2 2099.49
  2182.5 2090.86  2211.5 2091.59  2225.9 2094.63  2275.6 2086.01  2346.1 2082.30
  2575.1 2076.88  2722.3 2076.38  3185.1 2077.74  3225.2 2076.95  3339.8 2076.80
  4469.9 2079.66  4597.3 2081.69  4784.0 2077.56  4851.9 2071.43  4986.1 2072.19
  4993.4 2071.52  4995.5 2059.12  4996.1 2058.12  5027.5 2059.12  5043.0 2071.73
  5100.2 2070.65  5121.2 2075.15  5135.6 2082.77  5156.4 2086.14  5320.0 2096.47
#Mann=9,-1,0
  2025.0   0.035       0  2025.3    0.07       0  2031.3   0.035       0
  2722.3    0.07       0  3185.1   0.035       0  3225.2    0.07       0
  3339.8   0.035       0  4995.5   0.035       0  5027.5   0.035       0
Bank Sta=4995.5,5027.5
Exp/Cntr=0.3,0.1

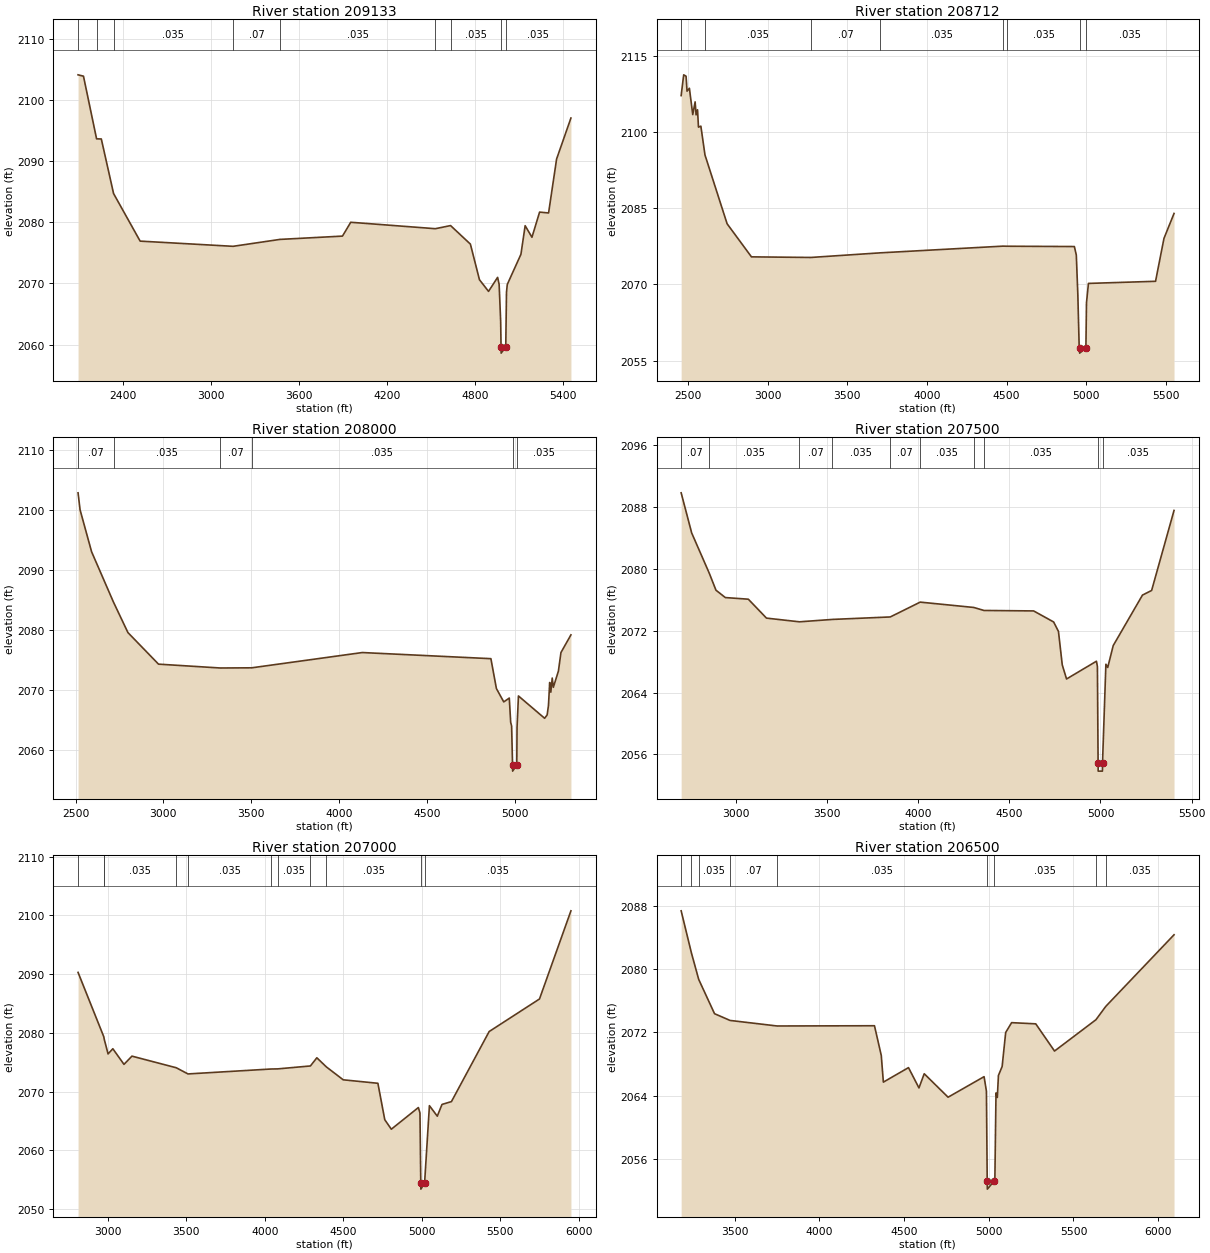
Type RM Length L Ch R = 1,209133,421,421,421
BEGIN DESCRIPTION:
Sweetwater Creek 417.0
END DESCRIPTION:
XS GIS Cut Line= 4
      1388845.52      6851209.85      1390775.31      6849757.24
      1391255.00      6849638.00      1391664.13      6849455.70
#Sta/Elev= 30
  2094.9 2104.07  2131.8 2103.85  2221.1 2093.61  2253.3 2093.59  2336.9 2084.67
  2517.8 2076.90  3150.8 2076.05  3470.1 2077.18  3896.2 2077.72  3952.5 2079.98
  4528.9 2078.93  4632.6 2079.44  4767.6 2076.41  4829.4 2070.59  4891.2 2068.69
  4953.1 2070.98  4963.4 2069.82  4973.7 2063.85  4976.5 2059.60  4977.1 2058.60
  5008.5 2059.60  5013.5 2068.54  5018.9 2069.82  5111.9 2074.75  5140.6 2079.42
  5187.0 2077.53  5239.0 2081.64  5300.2 2081.50  5354.9 2090.32  5452.5 2097.01
#Mann=9,-1,0
  2094.9   0.035       0  2221.1    0.07       0  2336.9   0.035       0
  3150.8    0.07       0  3470.1   0.035       0  4528.9    0.07       0
  4632.6   0.035       0  4976.5   0.035       0  5008.5   0.035       0
Bank Sta=4976.5,5008.5
Exp/Cntr=0.3,0.1

Type RM Length L Ch R = 1,208712,712,712,712
BEGIN DESCRIPTION:
Sweetwater Creek 416.0
END DESCRIPTION:
XS GIS Cut Line= 4
      1389089.11      6851283.41      1390412.90      6850389.58
      1391343.31      6849991.27      1391804.96      6849838.01
#Sta/Elev= 30
  2455.9 2107.18  2471.8 2111.27  2486.7 2111.00  2492.8 2108.05  2507.7 2108.62
  2528.7 2103.44  2543.7 2105.95  2549.7 2103.39  2558.7 2104.39  2564.7 2100.97
  2579.7 2101.17  2605.5 2095.50  2744.6 2081.95  2897.4 2075.44  3270.3 2075.32
  3706.8 2076.23  4477.2 2077.55  4505.3 2077.53  4925.7 2077.47  4937.9 2075.80
  4947.5 2068.01  4956.1 2057.49  4958.1 2057.49  4958.8 2056.49  4998.1 2057.49
  5001.8 2066.38  5014.1 2070.21  5435.6 2070.63  5488.5 2079.07  5551.7 2083.98
#Mann=8,-1,0
  2455.9    0.07       0  2605.5   0.035       0  3270.3    0.07       0
  3706.8   0.035       0  4477.2    0.07       0  4505.3   0.035       0
  4958.1   0.035       0  4998.1   0.035       0
Bank Sta=4958.1,4998.1
Exp/Cntr=0.3,0.1

Type RM Length L Ch R = 1,208000,500,500,500
BEGIN DESCRIPTION:
Sweetwater Creek 415.0
END DESCRIPTION:
XS GIS Cut Line= 3
      1389279.04      6851316.40      1391655.09      6850586.95
      1391904.98      6850388.02
#Sta/Elev= 30
  2514.5 2102.83  2526.0 2100.00  2591.5 2093.03  2716.3 2084.64  2798.3 2079.59
  2972.4 2074.34  3324.1 2073.70  3502.9 2073.73  4132.2 2076.27  4863.9 2075.25
  4895.3 2070.28  4937.1 2068.06  4968.5 2068.70  4976.6 2064.64  4981.8 2064.06
  4987.2 2057.55  4987.6 2056.55  5011.2 2057.55  5012.7 2063.81  5020.7 2069.05
  5169.7 2065.34  5184.1 2065.90  5191.6 2067.48  5198.5 2071.29  5204.9 2069.68
  5212.9 2072.03  5219.3 2070.49  5248.2 2073.19  5262.6 2076.27  5319.4 2079.21
#Mann=6,-1,0
  2514.5    0.07       0  2716.3   0.035       0  3324.1    0.07       0
  3502.9   0.035       0  4987.2   0.035       0  5011.2   0.035       0
Bank Sta=4987.2,5011.2
Exp/Cntr=0.3,0.1

Type RM Length L Ch R = 1,207500,500,500,500
BEGIN DESCRIPTION:
Sweetwater Creek 413.0
END DESCRIPTION:
XS GIS Cut Line= 5
      1389468.63      6851323.39      1391122.54      6850951.03
      1391267.58      6850934.28      1391705.27      6851068.10
      1392107.43      6851099.73
#Sta/Elev= 30
  2701.0 2089.87  2758.8 2084.67  2854.5 2079.50  2892.0 2077.26  2943.3 2076.31
  3069.2 2076.10  3168.8 2073.65  3349.8 2073.17  3530.2 2073.48  3847.6 2073.80
  4011.7 2075.72  4305.0 2075.03  4361.3 2074.64  4633.7 2074.58  4743.3 2073.15
  4769.7 2071.93  4790.6 2067.59  4814.1 2065.77  4978.1 2068.07  4983.3 2067.37
  4987.1 2054.84  4987.6 2053.84  5010.8 2053.84  5011.2 2054.84  5029.8 2067.68
  5039.9 2067.26  5069.9 2070.09  5230.4 2076.63  5280.6 2077.23  5403.4 2087.59
#Mann=10,-1,0
  2701.0    0.07       0  2854.5   0.035       0  3349.8    0.07       0
  3530.2   0.035       0  3847.6    0.07       0  4011.7   0.035       0
  4305.0    0.07       0  4361.3   0.035       0  4987.1   0.035       0
  5011.2   0.035       0
Bank Sta=4987.1,5011.2
Exp/Cntr=0.3,0.1

Type RM Length L Ch R = 1,207000,500,500,500
BEGIN DESCRIPTION:
Sweetwater Creek 445.0
END DESCRIPTION:
XS GIS Cut Line= 5
      1389526.79      6851374.30      1391082.47      6851107.47
      1391360.95      6851476.65      1391506.52      6851499.66
      1392455.04      6851538.00
#Sta/Elev= 30
  2811.8 2090.28  2975.7 2079.31  2978.2 2078.93  3002.8 2076.40  3033.2 2077.28
  3104.2 2074.62  3154.9 2076.02  3437.3 2074.04  3511.6 2072.99  4041.0 2073.83
  4082.7 2073.85  4290.9 2074.35  4331.9 2075.74  4392.8 2074.18  4499.8 2071.99
  4720.5 2071.40  4764.2 2065.20  4805.9 2063.58  4978.2 2067.27  4988.3 2066.34
  4993.5 2054.38  4994.0 2053.38  5017.6 2054.38  5048.5 2067.59  5098.6 2065.80
  5128.6 2067.80  5188.6 2068.28  5428.8 2080.21  5749.1 2085.75  5949.3 2100.76
#Mann=11,-1,0
  2811.8   0.035       0  2975.7    0.07       0  2978.2   0.035       0
  3437.3    0.07       0  3511.6   0.035       0  4041.0    0.07       0
  4082.7   0.035       0  4290.9    0.07       0  4392.8   0.035       0
  4993.5   0.035       0  5017.6   0.035       0
Bank Sta=4993.5,5017.6
Exp/Cntr=0.3,0.1

Type RM Length L Ch R = 1,206500,500,500,500
BEGIN DESCRIPTION:
Sweetwater Creek 412.0
END DESCRIPTION:
XS GIS Cut Line= 5
      1389628.85      6851419.23      1391057.36      6851556.29
      1391313.56      6851838.45      1391551.66      6852044.67
      1392330.53      6852036.00
#Sta/Elev= 30
  3183.8 2087.33  3244.2 2082.04  3287.3 2078.69  3380.9 2074.36  3472.4 2073.51
  3750.5 2072.81  4325.2 2072.84  4365.4 2069.09  4377.7 2065.73  4526.1 2067.56
  4587.9 2065.00  4618.9 2066.79  4759.8 2063.83  4972.4 2066.42  4986.2 2064.59
  4990.9 2053.24  4991.7 2052.24  5031.1 2053.24  5036.2 2053.67  5042.8 2064.37
  5050.5 2063.80  5057.1 2066.57  5079.0 2067.70  5099.9 2071.99  5135.0 2073.23
  5277.5 2073.08  5388.3 2069.65  5632.9 2073.60  5690.5 2075.27  6093.9 2084.31
#Mann=9,-1,0
  3183.8   0.035       0  3244.2    0.07       0  3287.3   0.035       0
  3472.4    0.07       0  3750.5   0.035       0  4990.9   0.035       0
  5031.1   0.035       0  5632.9    0.07       0  5690.5   0.035       0
Bank Sta=4990.9,5031.1
Exp/Cntr=0.3,0.1

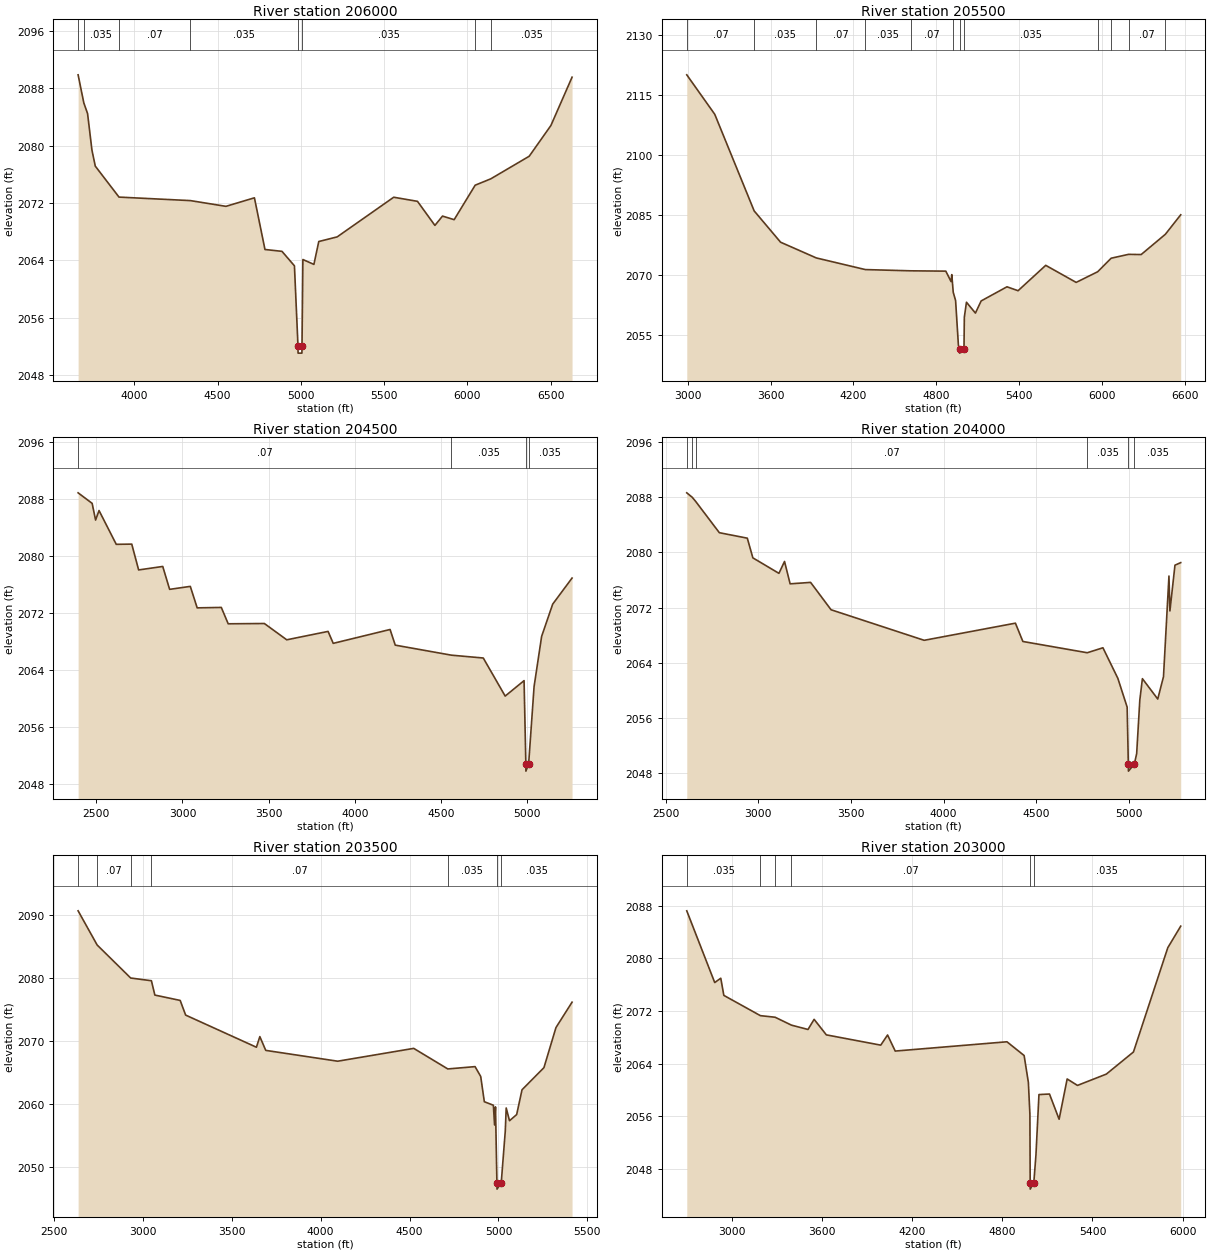
Type RM Length L Ch R = 1,206000,500,500,500
BEGIN DESCRIPTION:
Sweetwater Creek 411.0
END DESCRIPTION:
XS GIS Cut Line= 6
      1389652.49      6851507.12      1390726.20      6851620.97
      1390847.54      6851847.60      1390954.61      6851911.61
      1391397.83      6852062.99      1392431.87      6852112.00
#Sta/Elev= 30
  3663.2 2089.88  3697.5 2085.96  3720.0 2084.47  3746.2 2079.38  3766.3 2077.14
  3908.7 2072.82  4337.6 2072.33  4550.7 2071.53  4721.6 2072.72  4784.9 2065.51
  4887.0 2065.25  4961.8 2063.23  4983.1 2052.05  4983.5 2051.05  5006.7 2051.05
  5007.2 2052.05  5012.5 2064.11  5078.6 2063.43  5107.8 2066.62  5218.4 2067.27
  5557.7 2072.80  5700.4 2072.23  5805.0 2068.87  5850.6 2070.17  5920.6 2069.67
  6046.7 2074.48  6140.6 2075.37  6371.1 2078.52  6501.3 2082.81  6628.3 2089.55
#Mann=8,-1,0
  3663.2    0.07       0  3697.5   0.035       0  3908.7    0.07       0
  4337.6   0.035       0  4983.1   0.035       0  5007.2   0.035       0
  6046.7    0.07       0  6140.6   0.035       0
Bank Sta=4983.1,5007.2
Exp/Cntr=0.3,0.1

Type RM Length L Ch R = 1,205500,1000,1000,1000
BEGIN DESCRIPTION:
Sweetwater Creek 409.0
END DESCRIPTION:
XS GIS Cut Line= 5
      1388805.03      6851838.01      1390784.73      6852167.92
      1390844.81      6852152.97      1391089.88      6852084.06
      1392340.96      6852150.03
#Sta/Elev= 30
  2993.0 2120.04  3195.7 2110.16  3481.0 2085.98  3672.2 2078.15  3931.1 2074.21
  4285.9 2071.30  4612.9 2070.99  4868.5 2070.91  4906.6 2068.30  4911.7 2070.04
  4922.3 2065.62  4939.4 2063.54  4959.7 2052.39  4967.9 2051.39  4968.5 2050.39
  5000.1 2051.39  5002.7 2059.40  5018.0 2063.13  5082.9 2060.41  5124.4 2063.45
  5311.4 2066.99  5391.7 2066.01  5592.0 2072.36  5812.3 2068.09  5968.3 2070.76
  6065.5 2074.14  6191.5 2075.11  6282.9 2075.06  6458.1 2080.13  6569.3 2085.01
#Mann=12,-1,0
  2993.0    0.07       0  3481.0   0.035       0  3931.1    0.07       0
  4285.9   0.035       0  4612.9    0.07       0  4922.3   0.035       0
  4967.9   0.035       0  5000.1   0.035       0  5968.3    0.07       0
  6065.5   0.035       0  6191.5    0.07       0  6458.1   0.035       0
Bank Sta=4967.9,5000.1
Exp/Cntr=0.3,0.1

Type RM Length L Ch R = 1,204500,500,500,500
BEGIN DESCRIPTION:
Sweetwater Creek 408.0
END DESCRIPTION:
XS GIS Cut Line= 4
      1388963.54      6852636.30      1391262.05      6852600.47
      1391555.21      6852507.94      1391804.99      6852588.00
#Sta/Elev= 30
  2393.8 2088.90  2475.3 2087.42  2495.3 2085.07  2515.3 2086.41  2615.3 2081.66
  2705.3 2081.69  2745.3 2078.06  2885.3 2078.55  2925.3 2075.33  3045.3 2075.75
  3085.3 2072.73  3225.4 2072.79  3265.4 2070.49  3475.4 2070.53  3605.4 2068.24
  3845.4 2069.42  3875.4 2067.74  4205.5 2069.69  4235.5 2067.49  4561.6 2066.08
  4746.7 2065.68  4873.9 2060.33  4983.6 2062.50  4994.0 2050.78  4994.3 2049.78
  5010.1 2050.78  5041.8 2061.67  5085.6 2068.72  5149.8 2073.25  5262.3 2076.92
#Mann=4,-1,0
  2393.8    0.07       0  4561.6   0.035       0  4994.0   0.035       0
  5010.1   0.035       0
Bank Sta=4994,5010.1
Exp/Cntr=0.3,0.1

Type RM Length L Ch R = 1,204000,500,500,500
BEGIN DESCRIPTION:
Sweetwater Creek 407.0
END DESCRIPTION:
XS GIS Cut Line= 3
      1388960.01      6852688.31      1391335.18      6852907.93
      1391604.96      6852838.01
#Sta/Elev= 30
  2614.7 2088.60  2644.3 2087.95  2664.3 2087.30  2790.4 2082.83  2941.1 2082.04
  2971.2 2079.19  3111.8 2076.95  3141.9 2078.67  3172.1 2075.43  3282.5 2075.64
  3393.0 2071.68  3895.1 2067.26  4387.2 2069.74  4427.4 2067.09  4774.7 2065.46
  4859.2 2066.18  4939.6 2061.76  4989.8 2057.59  4996.2 2049.33  4996.8 2048.33
  5028.4 2049.33  5041.1 2050.85  5058.1 2058.61  5072.1 2061.71  5154.8 2058.76
  5185.8 2062.00  5215.3 2076.56  5220.4 2071.51  5247.7 2078.13  5278.7 2078.50
#Mann=6,-1,0
  2614.7    0.07       0  2644.3   0.035       0  2664.3    0.07       0
  4774.7   0.035       0  4996.2   0.035       0  5028.4   0.035       0
Bank Sta=4996.2,5028.4
Exp/Cntr=0.3,0.1

Type RM Length L Ch R = 1,203500,500,500,500
BEGIN DESCRIPTION:
Sweetwater Creek 406.0
END DESCRIPTION:
XS GIS Cut Line= 3
      1388871.08      6852887.30      1391192.96      6853326.74
      1391605.04      6853288.00
#Sta/Elev= 30
  2636.9 2090.73  2743.9 2085.30  2932.6 2080.05  3049.0 2079.62  3068.4 2077.34
  3210.8 2076.49  3241.4 2074.16  3639.4 2069.05  3658.6 2070.74  3691.8 2068.55
  4096.3 2066.83  4523.7 2068.87  4715.4 2065.60  4868.5 2065.97  4900.3 2064.41
  4920.7 2060.39  4971.5 2059.83  4978.3 2056.69  4983.4 2059.57  4991.5 2047.50
  4992.0 2046.50  5015.7 2047.50  5038.6 2055.77  5043.6 2059.40  5062.3 2057.37
  5102.5 2058.35  5132.6 2062.29  5255.9 2065.81  5323.5 2072.18  5413.9 2076.21
#Mann=7,-1,0
  2636.9   0.035       0  2743.9    0.07       0  2932.6   0.035       0
  3049.0    0.07       0  4715.4   0.035       0  4991.5   0.035       0
  5015.7   0.035       0
Bank Sta=4991.5,5015.7
Exp/Cntr=0.3,0.1

Type RM Length L Ch R = 1,203000,500,500,500
BEGIN DESCRIPTION:
Sweetwater Creek 405.0
END DESCRIPTION:
XS GIS Cut Line= 5
      1388762.80      6853318.67      1390843.79      6853719.70
      1391021.14      6853753.89      1391254.92      6853765.94
      1391954.98      6853488.01
#Sta/Elev= 30
  2700.1 2087.20  2886.1 2076.30  2926.4 2076.96  2946.8 2074.35  3190.2 2071.27
  3287.9 2071.03  3396.6 2069.83  3506.9 2069.17  3547.6 2070.71  3629.1 2068.35
  3991.0 2066.79  4036.4 2068.33  4087.4 2065.89  4830.8 2067.30  4945.2 2065.21
  4973.4 2061.14  4983.6 2056.29  4985.5 2045.91  4986.0 2044.91  5009.7 2045.91
  5023.9 2050.11  5043.9 2059.28  5114.0 2059.36  5178.0 2055.53  5231.6 2061.65
  5300.2 2060.67  5492.4 2062.39  5672.8 2065.75  5901.2 2081.59  5987.3 2084.87
#Mann=6,-1,0
  2700.1   0.035       0  3190.2    0.07       0  3287.9   0.035       0
  3396.6    0.07       0  4985.5   0.035       0  5009.7   0.035       0
Bank Sta=4985.5,5009.7
Exp/Cntr=0.3,0.1

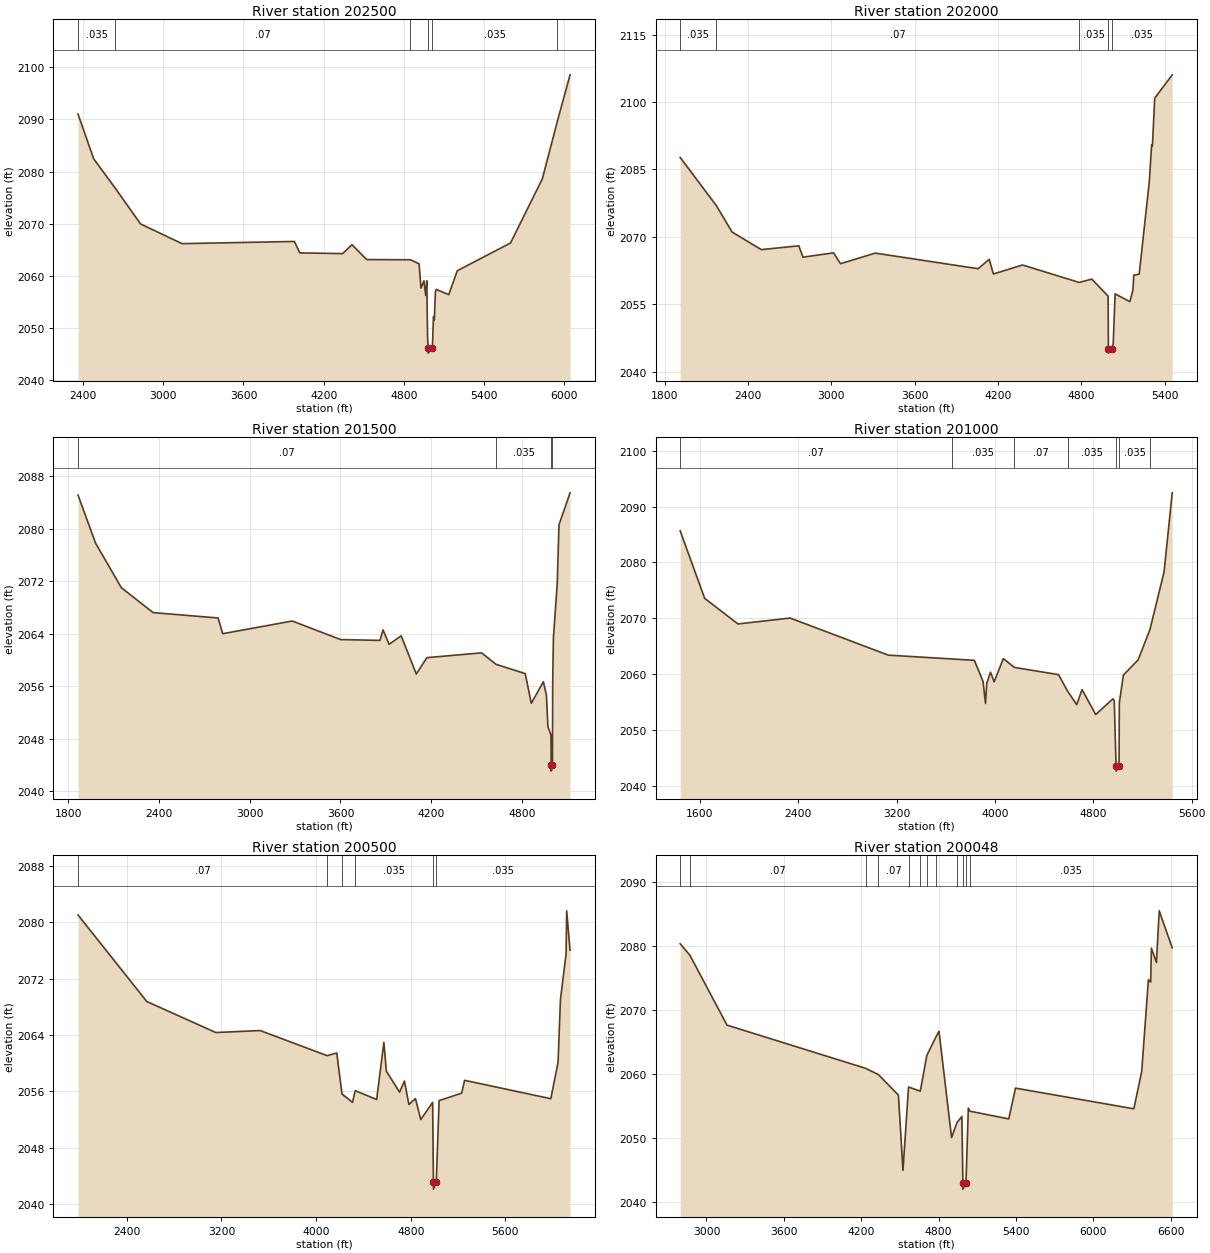
Type RM Length L Ch R = 1,202500,500,500,500
BEGIN DESCRIPTION:
Sweetwater Creek 404.0
END DESCRIPTION:
XS GIS Cut Line= 5
      1388737.58      6854205.69      1391014.79      6854282.94
      1391315.95      6854088.31      1391442.49      6853925.59
      1392195.87      6853562.60
#Sta/Elev= 30
  2362.9 2091.02  2480.4 2082.42  2639.7 2076.86  2830.6 2069.95  3140.8 2066.17
  3981.2 2066.59  4021.3 2064.40  4341.5 2064.26  4411.5 2065.97  4521.6 2063.12
  4848.9 2063.08  4913.6 2062.30  4927.4 2057.65  4949.9 2059.05  4963.1 2056.24
  4971.0 2059.04  4977.0 2048.24  4980.7 2046.18  4981.3 2045.18  5013.0 2046.18
  5021.1 2052.17  5027.5 2051.54  5035.6 2056.91  5042.0 2057.40  5135.2 2056.39
  5199.4 2060.98  5597.4 2066.30  5835.1 2078.59  5947.0 2089.58  6042.4 2098.54
#Mann=6,-1,0
  2362.9   0.035       0  2639.7    0.07       0  4848.9   0.035       0
  4980.7   0.035       0  5013.0   0.035       0  5947.0    0.07       0
Bank Sta=4980.7,5013
Exp/Cntr=0.3,0.1

Type RM Length L Ch R = 1,202000,500,500,500
BEGIN DESCRIPTION:
Sweetwater Creek 403.0
END DESCRIPTION:
XS GIS Cut Line= 4
      1388841.51      6854401.54      1391719.35      6854333.90
      1391799.59      6854140.41      1392204.97      6853938.02
#Sta/Elev= 30
  1911.9 2087.65  2172.1 2076.93  2285.5 2071.05  2495.6 2067.14  2765.6 2067.98
  2795.6 2065.46  3015.7 2066.42  3065.7 2064.00  3315.8 2066.36  4056.0 2062.89
  4136.0 2064.97  4166.0 2061.71  4376.1 2063.72  4783.2 2059.83  4874.3 2060.57
  4991.8 2056.79  4993.8 2045.10  4994.3 2044.10  5018.0 2045.10  5028.4 2046.16
  5042.1 2057.29  5148.3 2055.56  5170.7 2058.17  5176.3 2061.44  5215.5 2061.68
  5288.2 2082.29  5304.9 2090.39  5310.5 2090.22  5327.3 2100.85  5453.1 2106.04
#Mann=5,-1,0
  1911.9   0.035       0  2172.1    0.07       0  4783.2   0.035       0
  4993.8   0.035       0  5018.0   0.035       0
Bank Sta=4993.8,5018
Exp/Cntr=0.3,0.1

Type RM Length L Ch R = 1,201500,500,500,500
BEGIN DESCRIPTION:
Sweetwater Creek 402.0
END DESCRIPTION:
XS GIS Cut Line= 3
      1389008.75      6854588.71      1392142.53      6854476.11
      1392255.04      6854437.99
#Sta/Elev= 30
  1864.2 2085.10  1980.5 2077.77  2150.6 2071.00  2360.8 2067.20  2791.0 2066.38
  2821.1 2063.99  3281.4 2065.92  3601.6 2063.09  3861.7 2062.97  3881.8 2064.57
  3921.8 2062.37  4001.8 2063.66  4101.9 2057.85  4171.9 2060.34  4533.5 2061.07
  4629.8 2059.32  4822.4 2057.91  4862.4 2053.39  4942.4 2056.67  4962.4 2054.66
  4972.5 2049.84  4992.5 2048.55  4994.2 2044.06  4994.4 2043.06  5002.3 2044.06
  5003.9 2056.31  5008.8 2063.37  5034.3 2071.70  5045.5 2080.56  5118.8 2085.44
#Mann=4,-1,0
  1864.2    0.07       0  4629.8   0.035       0  4994.2   0.035       0
  5002.3   0.035       0
Bank Sta=4994.2,5002.3
Exp/Cntr=0.3,0.1

Type RM Length L Ch R = 1,201000,500,500,500
BEGIN DESCRIPTION:
Sweetwater Creek 401.0
END DESCRIPTION:
XS GIS Cut Line= 4
      1389503.20      6856955.57      1390909.38      6855064.48
      1392104.29      6854924.29      1392505.00      6854738.00
#Sta/Elev= 30
  1440.3 2085.66  1639.5 2073.57  1910.8 2068.99  2334.1 2070.05  3132.9 2063.41
  3653.7 2062.72  3832.8 2062.48  3903.2 2058.72  3923.4 2054.76  3933.4 2058.33
  3963.7 2060.35  3993.9 2058.63  4068.2 2062.79  4158.7 2061.21  4517.4 2059.92
  4590.7 2056.97  4665.6 2054.55  4708.7 2057.24  4819.5 2052.78  4960.4 2055.60
  4970.5 2055.23  4985.1 2043.65  4985.5 2042.65  5009.3 2043.65  5011.8 2054.86
  5044.9 2059.84  5164.9 2062.57  5261.2 2068.02  5375.7 2078.31  5441.9 2092.46
#Mann=7,-1,0
  1440.3    0.07       0  3653.7   0.035       0  4158.7    0.07       0
  4590.7   0.035       0  4985.1   0.035       0  5009.3   0.035       0
  5261.2    0.07       0
Bank Sta=4985.1,5009.3
Exp/Cntr=0.3,0.1

Type RM Length L Ch R = 1,200500,452,452,452
BEGIN DESCRIPTION:
Sweetwater Creek 400.0
END DESCRIPTION:
XS GIS Cut Line= 4
      1389742.84      6857221.40      1390884.60      6855514.19
      1391823.23      6855319.64      1392955.05      6855137.99
#Sta/Elev= 30
  1987.6 2081.03  2569.1 2068.75  3152.2 2064.35  3527.5 2064.63  4093.0 2061.07
  4174.6 2061.45  4218.7 2055.63  4307.4 2054.44  4330.7 2056.10  4511.6 2054.85
  4572.9 2062.96  4593.8 2058.86  4705.6 2055.89  4746.5 2057.46  4784.3 2054.14
  4839.6 2054.98  4884.6 2052.00  4985.0 2054.44  4991.5 2043.13  4991.9 2042.13
  5015.7 2043.13  5039.6 2054.69  5230.5 2055.75  5255.0 2057.57  5983.8 2054.96
  6045.0 2060.13  6065.2 2069.02  6112.8 2075.54  6117.8 2081.62  6146.3 2076.04
#Mann=6,-1,0
  1987.6    0.07       0  4093.0   0.035       0  4218.7   0.033       0
  4330.7   0.035       0  4991.5   0.035       0  5015.7   0.035       0
Bank Sta=4991.5,5015.7
Exp/Cntr=0.3,0.1

Type RM Length L Ch R = 1,200048,666,666,666
BEGIN DESCRIPTION:
Sweetwater Creek 399.0
END DESCRIPTION:
XS GIS Cut Line= 5
      1390130.64      6857235.25      1391405.00      6855688.00
      1391705.00      6855688.00      1391952.58      6855582.38
      1393086.96      6855077.05
#Sta/Elev= 30
  2796.0 2080.34  2870.6 2078.57  3159.2 2067.62  4233.3 2060.87  4333.1 2059.89
  4488.4 2056.68  4523.6 2044.92  4566.8 2057.94  4658.0 2057.30  4708.6 2062.88
  4782.1 2065.89  4803.0 2066.65  4900.5 2050.05  4942.1 2052.37  4980.5 2053.33
  4988.1 2042.98  4988.5 2041.98  5012.2 2042.98  5030.5 2054.65  5041.1 2054.17
  5343.9 2052.96  5396.2 2057.77  6313.8 2054.54  6374.8 2060.35  6426.8 2074.72
  6444.5 2074.34  6450.0 2079.66  6488.9 2077.42  6510.8 2085.49  6611.5 2079.71
#Mann=12,-1,0
  2796.0   0.035       0  2870.6    0.07       0  4233.3    0.16       0
  4333.1    0.07       0  4566.8    0.12       0  4658.0   0.035       0
  4708.6    0.12       0  4782.1   0.035       0  4942.1    0.12       0
  4988.1    0.07       0  5012.2    0.12       0  5041.1   0.035       0
Bank Sta=4988.1,5012.2
Exp/Cntr=0.3,0.1

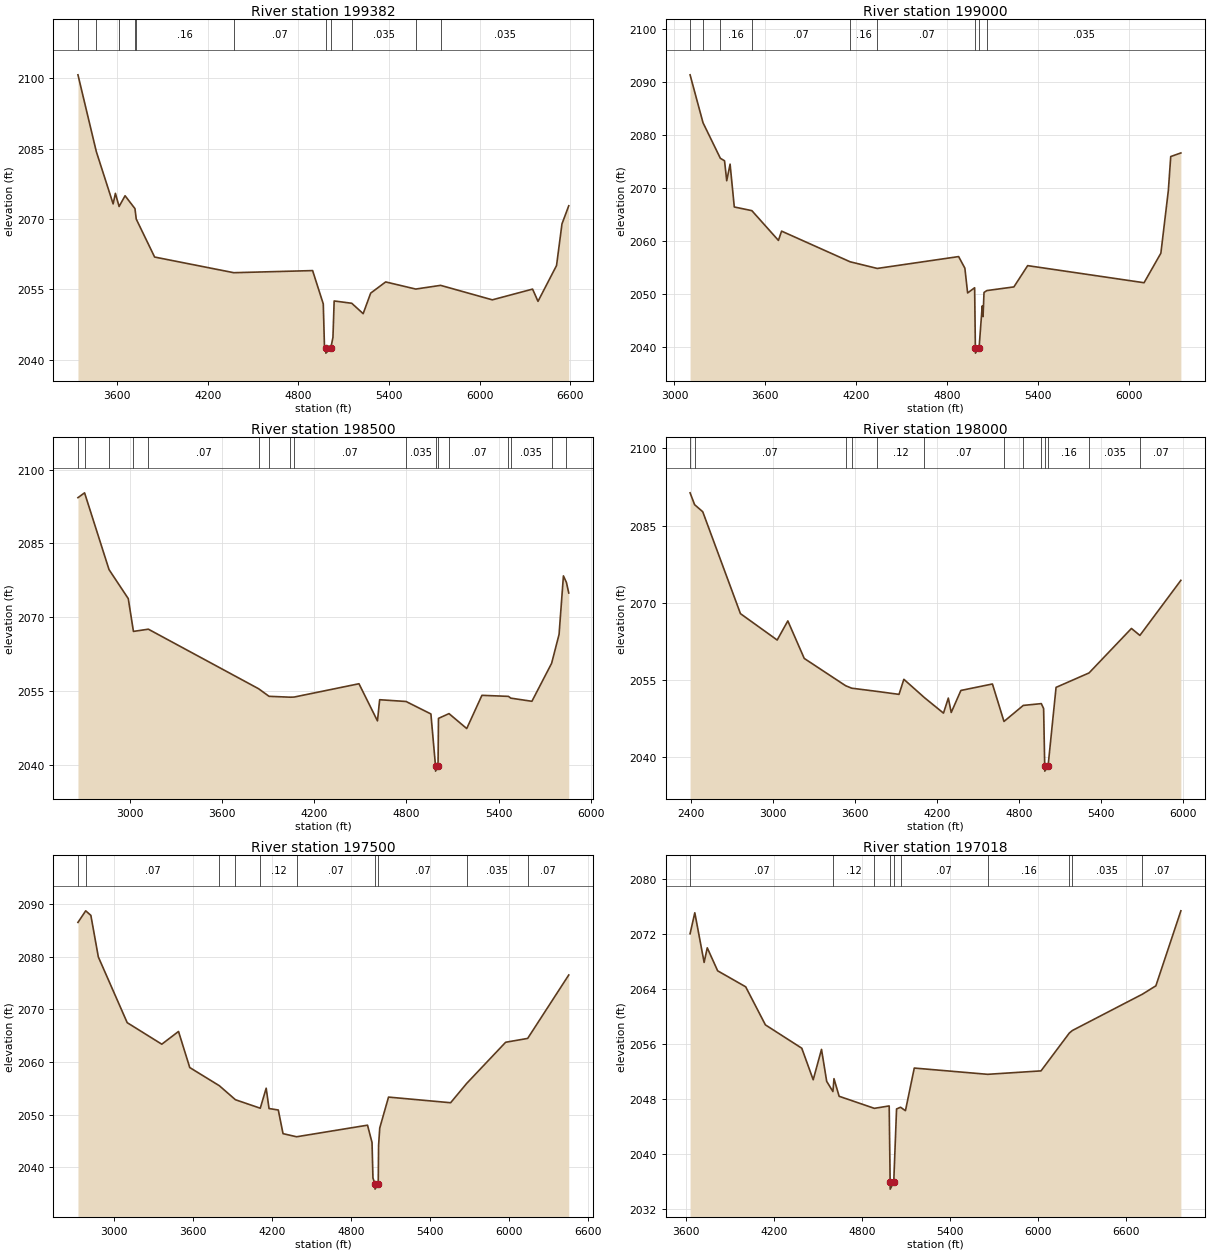
Type RM Length L Ch R = 1,199382,382,382,382
BEGIN DESCRIPTION:
Sweetwater Creek 398.0
END DESCRIPTION:
XS GIS Cut Line= 4
      1390904.98      6857588.03      1391733.97      6856264.73
      1392038.44      6855885.29      1393030.28      6855209.86
#Sta/Elev= 30
  3341.1 2100.74  3462.6 2084.36  3573.9 2073.20  3588.9 2075.45  3613.4 2072.65
  3652.9 2074.94  3718.4 2072.19  3726.9 2069.96  3848.5 2061.86  4372.3 2058.52
  4894.0 2058.97  4964.6 2051.86  4972.6 2042.58  4981.0 2042.36  4981.6 2041.36
  5013.7 2042.36  5028.6 2044.72  5036.6 2052.49  5152.9 2052.00  5228.6 2049.78
  5278.2 2054.16  5377.4 2056.55  5576.4 2055.03  5741.0 2055.82  6083.3 2052.73
  6349.7 2055.02  6385.6 2052.41  6508.3 2060.05  6544.2 2068.93  6589.1 2072.80
#Mann=11,-1,0
  3341.1    0.07       0  3462.6   0.035       0  3613.4    0.16       0
  3718.4    0.07       0  3726.9    0.16       0  4372.3    0.07       0
  4981.0    0.07       0  5013.7    0.07       0  5152.9   0.035       0
  5576.4    0.07       0  5741.0   0.035       0
Bank Sta=4981,5013.7
Exp/Cntr=0.3,0.1

Type RM Length L Ch R = 1,199000,500,500,500
BEGIN DESCRIPTION:
Sweetwater Creek 397.0
END DESCRIPTION:
XS GIS Cut Line= 5
      1391059.25      6857613.51      1392070.79      6856383.41
      1392145.00      6856088.19      1392285.68      6855774.11
      1393149.08      6855269.89
#Sta/Elev= 30
  3103.0 2091.38  3188.6 2082.32  3303.0 2075.61  3330.6 2075.14  3345.0 2071.37
  3367.2 2074.51  3395.0 2066.41  3510.9 2065.72  3686.5 2060.10  3707.3 2061.85
  4159.6 2056.06  4339.2 2054.80  4876.5 2057.04  4917.7 2054.84  4935.8 2050.17
  4982.1 2051.15  4987.0 2039.80  4987.5 2038.80  5011.5 2039.80  5032.1 2047.72
  5037.6 2045.69  5044.0 2050.26  5062.9 2050.62  5241.3 2051.31  5332.3 2055.33
  6100.9 2052.10  6211.9 2057.68  6261.3 2069.53  6277.0 2075.94  6344.0 2076.62
#Mann=9,-1,0
  3103.0    0.07       0  3188.6   0.035       0  3303.0    0.16       0
  3510.9    0.07       0  4159.6    0.16       0  4339.2    0.07       0
  4987.0    0.07       0  5011.5    0.07       0  5062.9   0.035       0
Bank Sta=4987,5011.5
Exp/Cntr=0.3,0.1

Type RM Length L Ch R = 1,198500,500,500,500
BEGIN DESCRIPTION:
Sweetwater Creek 396.0
END DESCRIPTION:
XS GIS Cut Line= 3
      1391055.49      6857731.31      1392613.26      6855988.01
      1393215.62      6855379.53
#Sta/Elev= 30
  2662.1 2094.29  2705.2 2095.27  2864.4 2079.69  2989.6 2073.80  3023.2 2067.15
  3120.4 2067.60  3837.6 2055.52  3905.7 2053.98  4045.1 2053.80  4069.0 2053.83
  4491.0 2056.53  4611.3 2048.99  4625.6 2053.29  4797.4 2052.93  4959.1 2050.40
  4989.2 2039.80  4989.5 2038.80  5005.5 2039.80  5008.3 2049.50  5076.9 2050.47
  5192.2 2047.44  5291.2 2054.18  5463.4 2053.97  5479.2 2053.61  5616.4 2052.97
  5744.7 2060.68  5793.2 2066.55  5821.5 2078.42  5841.4 2077.06  5856.2 2074.95
#Mann=17,-1,0
  2662.1   0.035       0  2705.2    0.07       0  2864.4   0.035       0
  3023.2    0.16       0  3120.4    0.07       0  3837.6    0.16       0
  3905.7    0.07       0  4045.1    0.12       0  4069.0    0.07       0
  4797.4   0.035       0  4989.2   0.035       0  5005.5   0.035       0
  5076.9    0.07       0  5463.4    0.16       0  5479.2   0.035       0
  5744.7    0.07       0  5841.4   0.035       0
Bank Sta=4989.2,5005.5
Exp/Cntr=0.3,0.1

Type RM Length L Ch R = 1,198000,500,500,500
BEGIN DESCRIPTION:
Sweetwater Creek 395.0
END DESCRIPTION:
XS GIS Cut Line= 5
      1391096.59      6857730.57      1392660.97      6856220.53
      1393053.08      6856043.76      1393280.03      6856012.27
      1393649.10      6855352.05
#Sta/Elev= 30
  2395.6 2091.37  2429.0 2089.06  2488.3 2087.69  2764.1 2067.87  3032.7 2062.74
  3110.6 2066.46  3230.7 2059.16  3533.5 2053.85  3578.0 2053.37  3765.5 2052.74
  3923.8 2052.17  3959.3 2055.10  4108.7 2051.56  4249.2 2048.52  4284.5 2051.45
  4305.8 2048.65  4376.5 2052.93  4607.1 2054.19  4691.7 2046.90  4832.6 2050.02
  4964.8 2050.37  4981.6 2049.41  4989.6 2038.24  4990.0 2037.24  5014.2 2038.24
  5072.6 2053.53  5313.9 2056.34  5623.9 2064.99  5685.7 2063.64  5985.5 2074.35
#Mann=13,-1,0
  2395.6   0.035       0  2429.0    0.07       0  3533.5    0.16       0
  3578.0    0.07       0  3765.5    0.12       0  4108.7    0.07       0
  4691.7   0.035       0  4832.6    0.07       0  4964.8    0.16       0
  4989.6    0.07       0  5014.2    0.16       0  5313.9   0.035       0
  5685.7    0.07       0
Bank Sta=4989.6,5014.2
Exp/Cntr=0.3,0.1

Type RM Length L Ch R = 1,197500,482,482,482
BEGIN DESCRIPTION:
Sweetwater Creek 394.0
END DESCRIPTION:
XS GIS Cut Line= 6
      1391126.39      6857757.79      1392398.21      6856633.86
      1392607.22      6856407.05      1392869.22      6856473.92
      1393035.93      6856430.16      1393754.68      6855371.44
#Sta/Elev= 30
  2723.9 2086.50  2782.8 2088.70  2821.9 2087.84  2878.8 2079.94  3098.0 2067.47
  3360.7 2063.38  3487.8 2065.80  3573.1 2058.95  3797.9 2055.50  3920.2 2052.84
  4108.7 2051.23  4153.7 2055.03  4175.4 2051.17  4245.7 2050.89  4281.7 2046.40
  4384.8 2045.81  4923.4 2048.01  4957.7 2044.72  4964.7 2037.98  4980.2 2036.87
  4980.7 2035.87  5004.8 2036.87  5007.4 2044.14  5016.3 2047.48  5083.0 2053.34
  5554.6 2052.27  5676.8 2055.94  5972.7 2063.75  6139.9 2064.48  6452.0 2076.52
#Mann=10,-1,0
  2723.9   0.035       0  2782.8    0.07       0  3797.9    0.16       0
  3920.2    0.07       0  4108.7    0.12       0  4384.8    0.07       0
  4980.2    0.07       0  5004.8    0.07       0  5676.8   0.035       0
  6139.9    0.07       0
Bank Sta=4980.2,5004.8
Exp/Cntr=0.3,0.1

Type RM Length L Ch R = 1,197018,518,518,518
BEGIN DESCRIPTION:
Sweetwater Creek 393.0
END DESCRIPTION:
XS GIS Cut Line= 6
      1391535.91      6857674.32      1392377.81      6856807.38
      1392545.18      6856803.37      1392659.39      6856789.21
      1393119.25      6856565.63      1393832.48      6855431.93
#Sta/Elev= 30
  3630.4 2072.00  3662.6 2075.05  3726.1 2067.84  3747.4 2069.96  3818.2 2066.62
  4009.0 2064.30  4143.3 2058.77  4391.0 2055.38  4468.7 2050.80  4525.3 2055.21
  4560.6 2050.57  4602.9 2049.09  4610.2 2050.96  4645.4 2048.40  4885.1 2046.65
  4986.1 2047.00  4992.6 2035.92  4993.0 2034.92  5017.1 2035.92  5036.3 2046.56
  5063.3 2046.81  5096.8 2046.31  5156.9 2052.50  5656.3 2051.59  6019.8 2052.09
  6212.4 2057.58  6233.1 2057.95  6710.5 2063.23  6801.9 2064.44  6972.1 2075.33
#Mann=10,-1,0
  3630.4    0.07       0  4602.9    0.12       0  4885.1    0.07       0
  4992.6    0.07       0  5017.1    0.07       0  5063.3    0.07       0
  5656.3    0.16       0  6212.4    0.07       0  6233.1   0.035       0
  6710.5    0.07       0
Bank Sta=4992.6,5017.1
Exp/Cntr=0.3,0.1