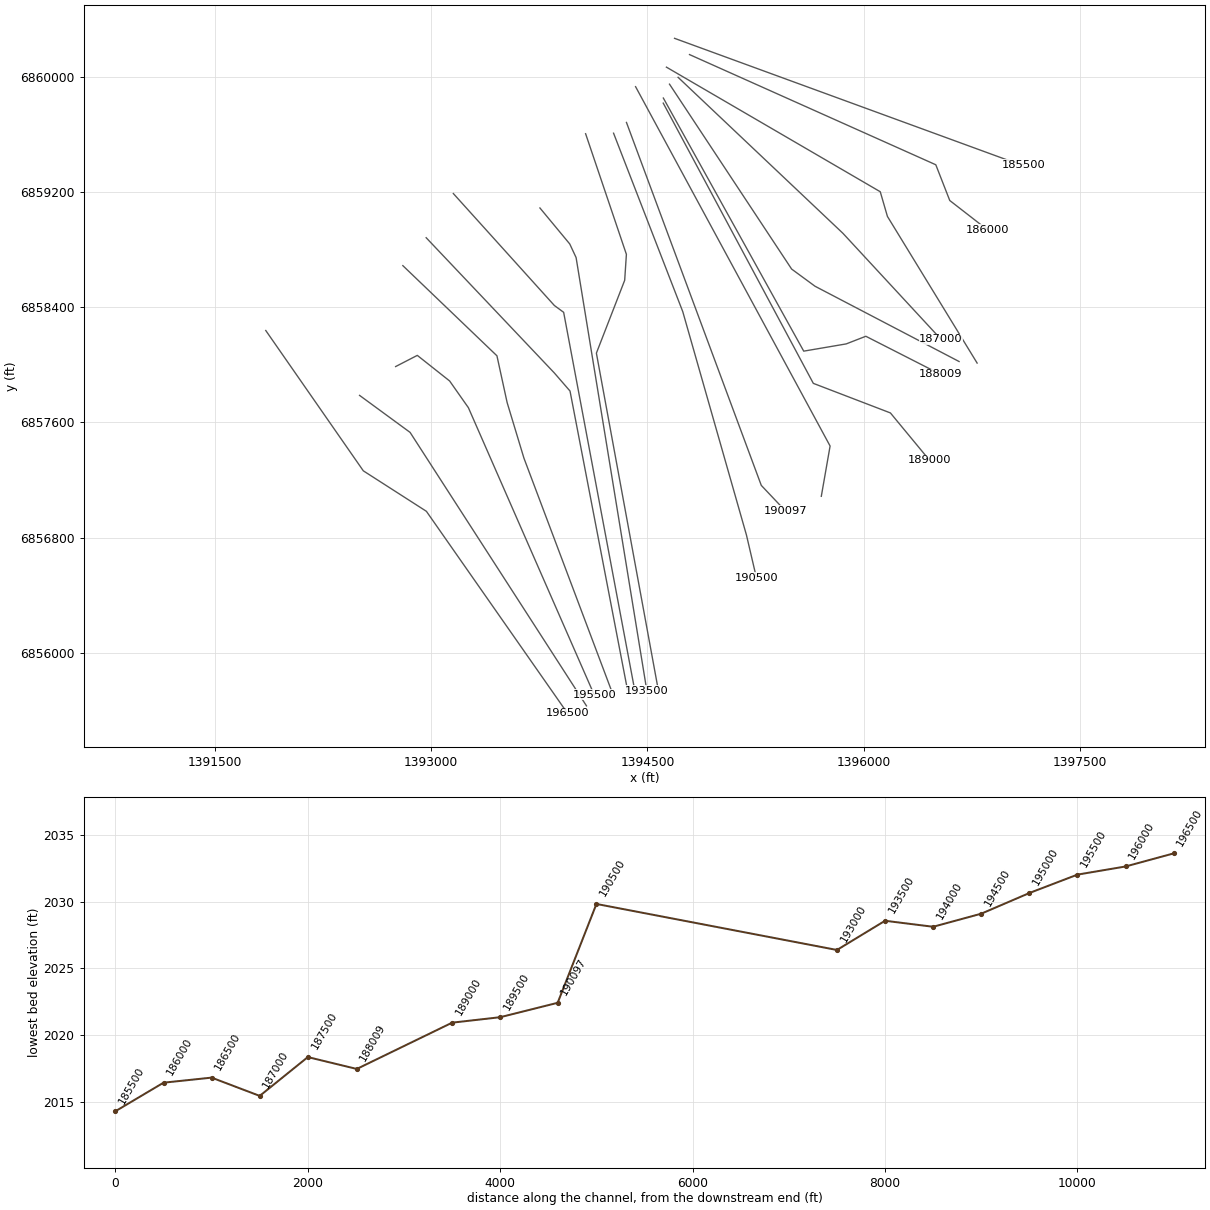
HEC-RAS study Sweetwater Creek.prj: Sweetwater Creek Base Level Engineering

--- Sweetwater Creek.g01 (geometry) --- (continued)

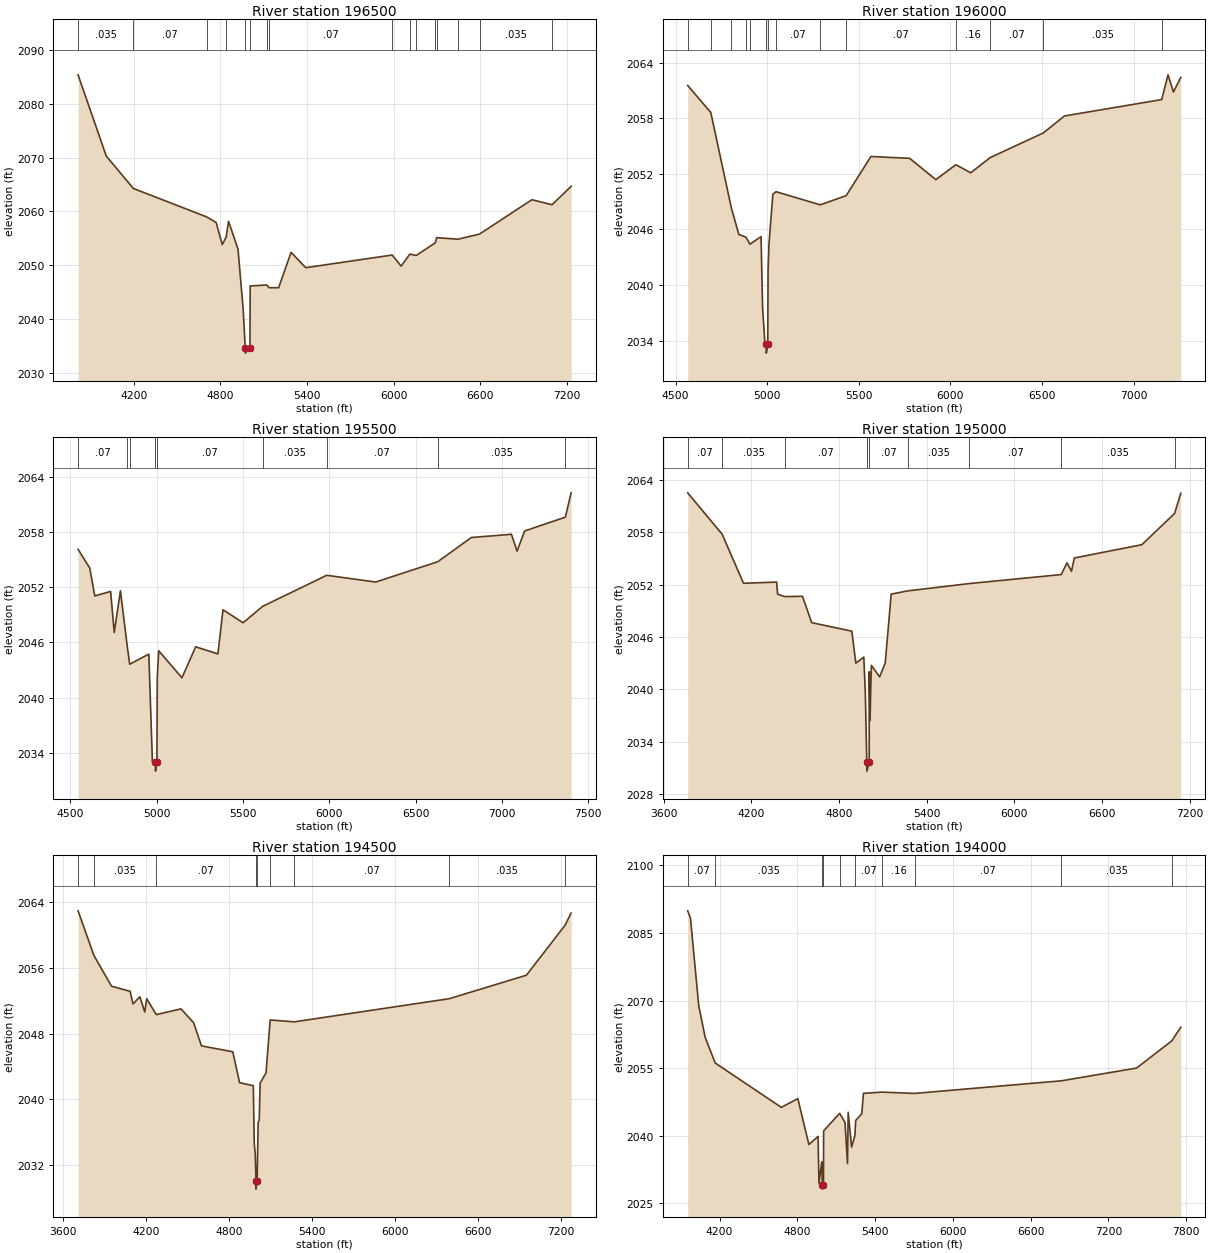
Type RM Length L Ch R = 1,196500,500,500,500
BEGIN DESCRIPTION:
Sweetwater Creek 392.0
END DESCRIPTION:
XS GIS Cut Line= 4
      1391854.97      6858238.04      1392531.01      6857264.67
      1392968.14      6856983.89      1393946.74      6855582.14
#Sta/Elev= 30
  3814.9 2085.45  4009.8 2070.34  4197.6 2064.29  4704.4 2059.00  4770.5 2057.97
  4813.3 2053.83  4840.3 2055.21  4857.0 2058.16  4922.5 2052.98  4958.3 2041.72
  4972.3 2034.62  4972.9 2033.62  5005.0 2034.62  5006.9 2046.13  5121.7 2046.31
  5137.6 2045.80  5203.7 2045.80  5290.0 2052.40  5391.3 2049.53  5990.1 2051.89
  6052.1 2049.83  6112.4 2052.06  6156.6 2051.81  6288.8 2054.17  6297.9 2055.12
  6445.6 2054.84  6594.7 2055.79  6957.5 2062.19  7097.0 2061.26  7229.1 2064.68
#Mann=16,-1,0
  3814.9   0.035       0  4197.6    0.07       0  4704.4   0.035       0
  4840.3    0.07       0  4972.3    0.07       0  5005.0    0.07       0
  5121.7   0.035       0  5137.6    0.07       0  5990.1    0.16       0
  6112.4    0.07       0  6156.6    0.16       0  6288.8    0.07       0
  6297.9    0.16       0  6445.6    0.07       0  6594.7   0.035       0
  7097.0    0.07       0
Bank Sta=4972.3,5005
Exp/Cntr=0.3,0.1

Type RM Length L Ch R = 1,196000,500,500,500
BEGIN DESCRIPTION:
Sweetwater Creek 391.0
END DESCRIPTION:
XS GIS Cut Line= 3
      1392505.02      6857787.99      1392855.13      6857531.34
      1394077.49      6855634.36
#Sta/Elev= 30
  4565.9 2061.52  4691.8 2058.61  4804.4 2048.28  4844.9 2045.44  4883.0 2045.16
  4905.7 2044.40  4966.1 2045.21  4974.6 2037.57  4987.4 2033.64  4994.7 2033.64
  4994.8 2032.64  5002.8 2033.64  5004.5 2041.58  5009.5 2044.46  5030.6 2049.78
  5047.5 2050.06  5289.3 2048.64  5430.6 2049.63  5565.9 2053.86  5777.2 2053.66
  5920.0 2051.36  6029.4 2052.97  6110.3 2052.10  6216.8 2053.74  6506.7 2056.40
  6621.9 2058.23  7152.7 2060.00  7187.2 2062.67  7216.7 2060.82  7256.7 2062.39
#Mann=14,-1,0
  4565.9   0.035       0  4691.8    0.07       0  4804.4    0.16       0
  4883.0    0.07       0  4905.7   0.035       0  4994.7   0.035       0
  5002.8   0.035       0  5047.5    0.07       0  5289.3    0.16       0
  5430.6    0.07       0  6029.4    0.16       0  6216.8    0.07       0
  6506.7   0.035       0  7152.7    0.07       0
Bank Sta=4994.7,5002.8
Exp/Cntr=0.3,0.1

Type RM Length L Ch R = 1,195500,500,500,500
BEGIN DESCRIPTION:
Sweetwater Creek 390.0
END DESCRIPTION:
XS GIS Cut Line= 5
      1392754.98      6857987.99      1392905.15      6858065.51
      1393129.16      6857888.03      1393259.32      6857702.50
      1394130.91      6855711.33
#Sta/Elev= 30
  4545.2 2056.11  4612.7 2054.07  4642.1 2051.04  4733.7 2051.53  4754.6 2047.08
  4790.6 2051.60  4827.9 2045.88  4844.1 2043.63  4954.9 2044.73  4975.7 2033.03
  4993.5 2033.03  4993.6 2032.03  5001.7 2033.03  5003.8 2042.20  5012.2 2045.09
  5146.7 2042.16  5226.3 2045.52  5355.0 2044.75  5384.4 2049.54  5500.8 2048.13
  5614.1 2049.91  5984.9 2053.28  6268.6 2052.55  6627.9 2054.75  6822.1 2057.38
  7054.5 2057.73  7087.3 2055.90  7130.9 2058.09  7366.9 2059.59  7400.2 2062.23
#Mann=9,-1,0
  4545.2    0.07       0  4827.9   0.035       0  4844.1    0.07       0
  4993.5    0.07       0  5001.7    0.07       0  5614.1   0.035       0
  5984.9    0.07       0  6627.9   0.035       0  7366.9    0.07       0
Bank Sta=4993.5,5001.7
Exp/Cntr=0.3,0.1

Type RM Length L Ch R = 1,195000,500,500,500
BEGIN DESCRIPTION:
Sweetwater Creek 389.0
END DESCRIPTION:
XS GIS Cut Line= 5
      1392805.00      6858688.00      1393457.04      6858062.64
      1393527.78      6857737.91      1393644.08      6857352.84
      1394255.32      6855728.16
#Sta/Elev= 30
  3764.2 2062.52  3999.8 2057.78  4146.1 2052.16  4372.6 2052.30  4379.5 2050.91
  4428.7 2050.64  4549.3 2050.67  4612.8 2047.65  4887.3 2046.68  4914.7 2043.01
  4969.2 2043.71  4979.4 2039.69  4989.7 2031.65  4990.0 2030.65  5006.1 2031.65
  5006.4 2042.04  5011.6 2036.44  5020.8 2042.76  5077.6 2041.45  5115.7 2043.02
  5156.6 2050.92  5269.3 2051.29  5692.2 2052.13  6319.7 2053.16  6359.9 2054.51
  6390.4 2053.53  6409.7 2055.06  6872.0 2056.58  7096.1 2060.16  7138.1 2062.47
#Mann=9,-1,0
  3764.2    0.07       0  3999.8   0.035       0  4428.7    0.07       0
  4989.7    0.07       0  5006.1    0.07       0  5269.3   0.035       0
  5692.2    0.07       0  6319.7   0.035       0  7096.1    0.07       0
Bank Sta=4989.7,5006.1
Exp/Cntr=0.3,0.1

Type RM Length L Ch R = 1,194500,500,500,500
BEGIN DESCRIPTION:
Sweetwater Creek 388.0
END DESCRIPTION:
XS GIS Cut Line= 4
      1392966.64      6858881.70      1393854.59      6857943.88
      1393963.54      6857818.16      1394361.35      6855747.08
#Sta/Elev= 30
  3708.5 2062.94  3823.4 2057.50  3950.3 2053.78  4085.0 2053.15  4106.1 2051.62
  4155.4 2052.49  4191.0 2050.64  4205.2 2052.25  4274.3 2050.32  4452.8 2051.02
  4544.6 2049.33  4601.2 2046.52  4827.8 2045.80  4877.1 2042.04  4976.2 2041.68
  4983.1 2034.62  4990.4 2033.32  4995.6 2030.10  4995.7 2029.10  5003.8 2030.10
  5011.3 2037.22  5019.0 2037.50  5025.6 2042.00  5068.3 2043.24  5098.1 2049.67
  5272.5 2049.44  6394.7 2052.26  6951.8 2055.11  7230.6 2061.17  7275.3 2062.66
#Mann=9,-1,0
  3708.5    0.07       0  3823.4   0.035       0  4274.3    0.07       0
  4995.6    0.07       0  5003.8    0.07       0  5098.1    0.16       0
  5272.5    0.07       0  6394.7   0.035       0  7230.6    0.07       0
Bank Sta=4995.6,5003.8
Exp/Cntr=0.3,0.1

Type RM Length L Ch R = 1,194000,500,500,500
BEGIN DESCRIPTION:
Sweetwater Creek 387.0
END DESCRIPTION:
XS GIS Cut Line= 4
      1393154.97      6859188.04      1393854.97      6858411.60
      1393919.40      6858364.19      1394413.87      6855732.64
#Sta/Elev= 30
  3954.6 2089.91  3975.9 2088.29  4039.5 2068.90  4089.3 2061.82  4166.8 2056.12
  4677.0 2046.27  4804.0 2048.22  4889.2 2038.02  4960.2 2039.83  4966.9 2029.47
  4988.6 2034.19  4993.3 2029.12  4993.5 2028.12  5001.5 2029.12  5003.1 2041.06
  5126.7 2044.95  5167.7 2042.95  5187.2 2033.79  5192.3 2045.19  5218.6 2037.45
  5244.4 2040.01  5249.9 2043.33  5297.4 2044.88  5310.1 2049.39  5453.9 2049.66
  5705.4 2049.37  6837.4 2052.17  7416.6 2055.00  7688.1 2061.03  7757.6 2064.06
#Mann=10,-1,0
  3954.6    0.07       0  4166.8   0.035       0  4993.3    0.07       0
  5001.5   0.035       0  5126.7   0.035       0  5244.4    0.07       0
  5453.9    0.16       0  5705.4    0.07       0  6837.4   0.035       0
  7688.1    0.07       0
Bank Sta=4993.3,5001.5
Exp/Cntr=0.3,0.1

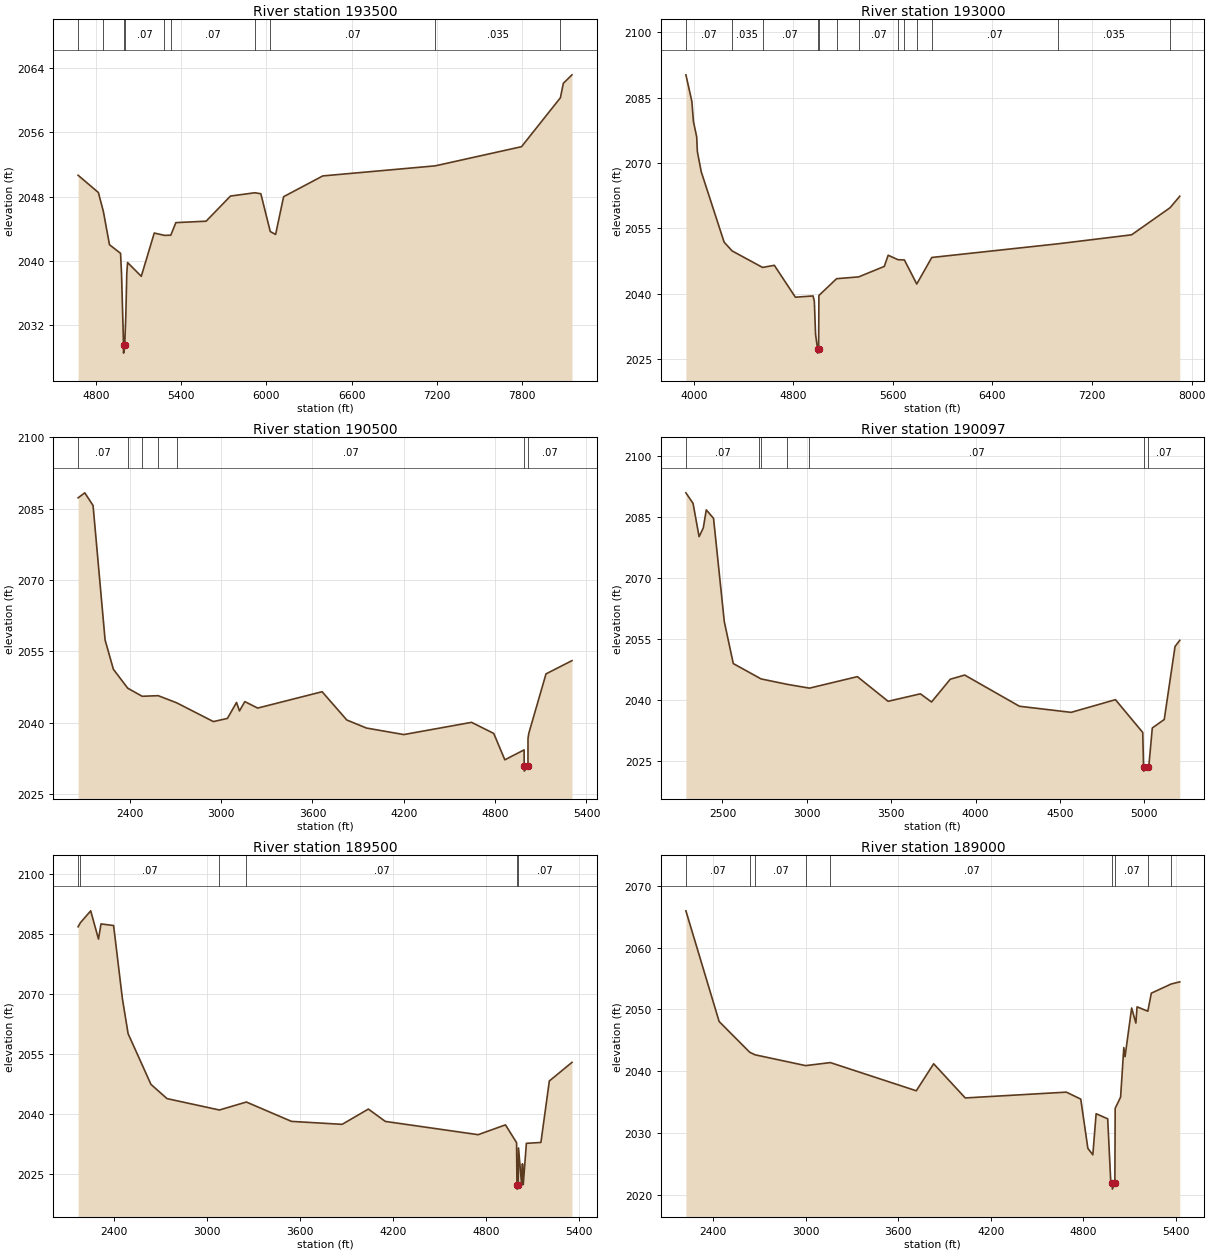
Type RM Length L Ch R = 1,193500,500,500,500
BEGIN DESCRIPTION:
Sweetwater Creek 386.0
END DESCRIPTION:
XS GIS Cut Line= 4
      1393754.99      6859088.01      1393961.70      6858838.39
      1394005.62      6858744.06      1394496.24      6855737.79
#Sta/Elev= 30
  4675.9 2050.65  4818.6 2048.51  4853.7 2046.15  4896.6 2042.03  4974.5 2040.96
  4981.3 2038.50  4995.5 2029.57  4995.6 2028.57  5003.7 2029.57  5011.5 2033.19
  5018.3 2038.44  5023.8 2039.82  5120.3 2038.11  5211.5 2043.48  5283.3 2043.19
  5327.8 2043.21  5363.5 2044.77  5576.3 2044.95  5747.8 2048.07  5918.9 2048.48
  5961.3 2048.36  6027.6 2043.67  6065.1 2043.30  6121.5 2047.99  6397.0 2050.57
  7188.1 2051.82  7795.3 2054.20  8068.8 2060.28  8089.1 2062.06  8150.1 2063.12
#Mann=10,-1,0
  4675.9   0.035       0  4853.7    0.07       0  4995.5    0.07       0
  5003.7    0.07       0  5283.3    0.16       0  5327.8    0.07       0
  5918.9    0.16       0  6027.6    0.07       0  7188.1   0.035       0
  8068.8    0.07       0
Bank Sta=4995.5,5003.7
Exp/Cntr=0.3,0.1

Type RM Length L Ch R = 1,193000,2500,2500,2500
BEGIN DESCRIPTION:
Sweetwater Creek 385.0
END DESCRIPTION:
XS GIS Cut Line= 5
      1394071.54      6859603.19      1394354.22      6858766.40
      1394342.38      6858586.53      1394146.28      6858081.05
      1394572.93      6855757.17
#Sta/Elev= 30
  3936.5 2090.27  3984.2 2084.21  3997.1 2079.56  4023.3 2076.02  4028.6 2072.64
  4060.0 2068.00  4243.5 2051.87  4307.7 2049.85  4552.7 2046.05  4647.1 2046.54
  4816.3 2039.22  4958.4 2039.51  4968.5 2038.32  4978.5 2030.64  4994.8 2027.38
  4994.9 2026.38  5003.0 2027.38  5005.2 2039.61  5147.4 2043.47  5324.8 2043.88
  5530.6 2046.29  5561.7 2048.85  5640.8 2047.83  5692.3 2047.77  5791.4 2042.25
  5912.4 2048.34  6930.1 2051.49  7517.7 2053.54  7826.9 2059.76  7904.9 2062.40
#Mann=13,-1,0
  3936.5    0.07       0  4307.7   0.035       0  4552.7    0.07       0
  4994.8    0.07       0  5003.0    0.07       0  5147.4   0.035       0
  5324.8    0.07       0  5640.8   0.035       0  5692.3    0.07       0
  5791.4    0.16       0  5912.4    0.07       0  6930.1   0.035       0
  7826.9    0.07       0
Bank Sta=4994.8,5003
Exp/Cntr=0.3,0.1

Type RM Length L Ch R = 1,190500,403,403,403
BEGIN DESCRIPTION:
Sweetwater Creek 380.0
END DESCRIPTION:
XS GIS Cut Line= 4
      1394265.34      6859606.75      1394744.91      6858368.83
      1395186.38      6856818.74      1395255.61      6856521.90
#Sta/Elev= 30
  2060.7 2087.31  2104.5 2088.36  2158.9 2085.70  2238.0 2057.40  2292.5 2051.25
  2386.8 2047.27  2481.8 2045.57  2586.8 2045.70  2708.6 2044.19  2949.5 2040.25
  3041.6 2040.92  3101.4 2044.28  3120.6 2042.49  3155.9 2044.45  3240.3 2043.09
  3663.5 2046.53  3825.8 2040.58  3955.1 2038.89  4200.1 2037.52  4645.1 2040.09
  4790.9 2037.76  4863.8 2032.21  4990.4 2034.30  4991.0 2030.83  4991.4 2029.83
  5015.6 2030.83  5016.0 2036.73  5021.3 2037.80  5134.2 2050.28  5304.8 2053.07
#Mann=7,-1,0
  2060.7    0.07       0  2386.8   0.035       0  2481.8    0.07       0
  2586.8   0.035       0  2708.6    0.07       0  4991.0    0.07       0
  5015.6    0.07       0
Bank Sta=4991,5015.6
Exp/Cntr=0.3,0.1

Type RM Length L Ch R = 1,190097,597,597,597
BEGIN DESCRIPTION:
Sweetwater Creek 379.0
END DESCRIPTION:
XS GIS Cut Line= 3
      1394354.74      6859681.33      1395289.06      6857163.65
      1395455.00      6856988.00
#Sta/Elev= 30
  2283.1 2090.93  2325.5 2088.34  2361.3 2080.14  2386.2 2082.30  2404.0 2086.74
  2447.0 2084.63  2510.6 2059.25  2564.0 2048.90  2718.2 2045.36  2728.7 2045.12
  2882.7 2043.79  3015.6 2042.85  3299.4 2045.68  3481.6 2039.61  3672.9 2041.45
  3739.0 2039.44  3849.8 2045.04  3935.6 2046.07  4259.9 2038.39  4566.4 2036.89
  4829.1 2040.01  4990.7 2031.94  4995.6 2023.42  4996.0 2022.42  5020.3 2023.42
  5026.3 2023.42  5047.4 2033.05  5118.2 2035.13  5182.1 2053.11  5210.2 2054.62
#Mann=7,-1,0
  2283.1    0.07       0  2718.2   0.035       0  2728.7    0.07       0
  2882.7   0.035       0  3015.6    0.07       0  4995.6    0.07       0
  5020.3    0.07       0
Bank Sta=4995.6,5020.3
Exp/Cntr=0.3,0.1

Type RM Length L Ch R = 1,189500,500,500,500
BEGIN DESCRIPTION:
Sweetwater Creek 378.0
END DESCRIPTION:
XS GIS Cut Line= 3
      1394417.85      6859929.56      1395765.93      6857436.72
      1395705.00      6857088.00
#Sta/Elev= 30
  2166.0 2086.82  2180.5 2087.82  2247.3 2090.80  2297.6 2083.75  2313.8 2087.53
  2395.1 2087.13  2452.0 2068.84  2488.8 2060.14  2636.3 2047.48  2740.0 2043.93
  3078.2 2041.09  3252.0 2043.08  3543.4 2038.25  3870.4 2037.51  4039.7 2041.32
  4149.1 2038.24  4748.4 2034.93  4924.6 2037.38  4996.4 2032.94  4998.8 2022.34
  4999.0 2021.34  5007.0 2022.34  5008.9 2031.62  5029.2 2022.34  5034.3 2027.66
  5039.4 2022.45  5059.6 2032.77  5153.4 2032.99  5207.8 2048.33  5354.0 2052.98
#Mann=6,-1,0
  2166.0   0.035       0  2180.5    0.07       0  3078.2   0.035       0
  3252.0    0.07       0  4998.8    0.07       0  5007.0    0.07       0
Bank Sta=4998.8,5007
Exp/Cntr=0.3,0.1

Type RM Length L Ch R = 1,189000,991,991,991
BEGIN DESCRIPTION:
Sweetwater Creek 377.0
END DESCRIPTION:
XS GIS Cut Line= 4
      1394609.60      6859815.32      1395649.68      6857871.41
      1396183.89      6857666.30      1396455.02      6857337.97
#Sta/Elev= 30
  2223.1 2065.95  2438.6 2048.05  2636.5 2043.08  2671.4 2042.66  2999.7 2040.91
  3159.8 2041.40  3717.1 2036.84  3829.9 2041.21  4034.7 2035.68  4690.5 2036.62
  4783.8 2035.49  4829.8 2027.53  4861.9 2026.48  4883.4 2033.13  4958.5 2032.30
  4977.9 2022.31  4988.4 2021.93  4988.7 2020.93  5004.9 2021.93  5006.9 2034.00
  5042.1 2035.82  5062.9 2043.83  5070.8 2042.35  5113.8 2050.23  5141.1 2047.79
  5148.9 2050.42  5218.6 2049.71  5241.4 2052.63  5369.7 2054.11  5425.8 2054.46
#Mann=9,-1,0
  2223.1    0.07       0  2636.5   0.035       0  2671.4    0.07       0
  2999.7   0.035       0  3159.8    0.07       0  4988.4    0.07       0
  5004.9    0.07       0  5218.6   0.035       0  5369.7    0.07       0
Bank Sta=4988.4,5004.9
Exp/Cntr=0.3,0.1

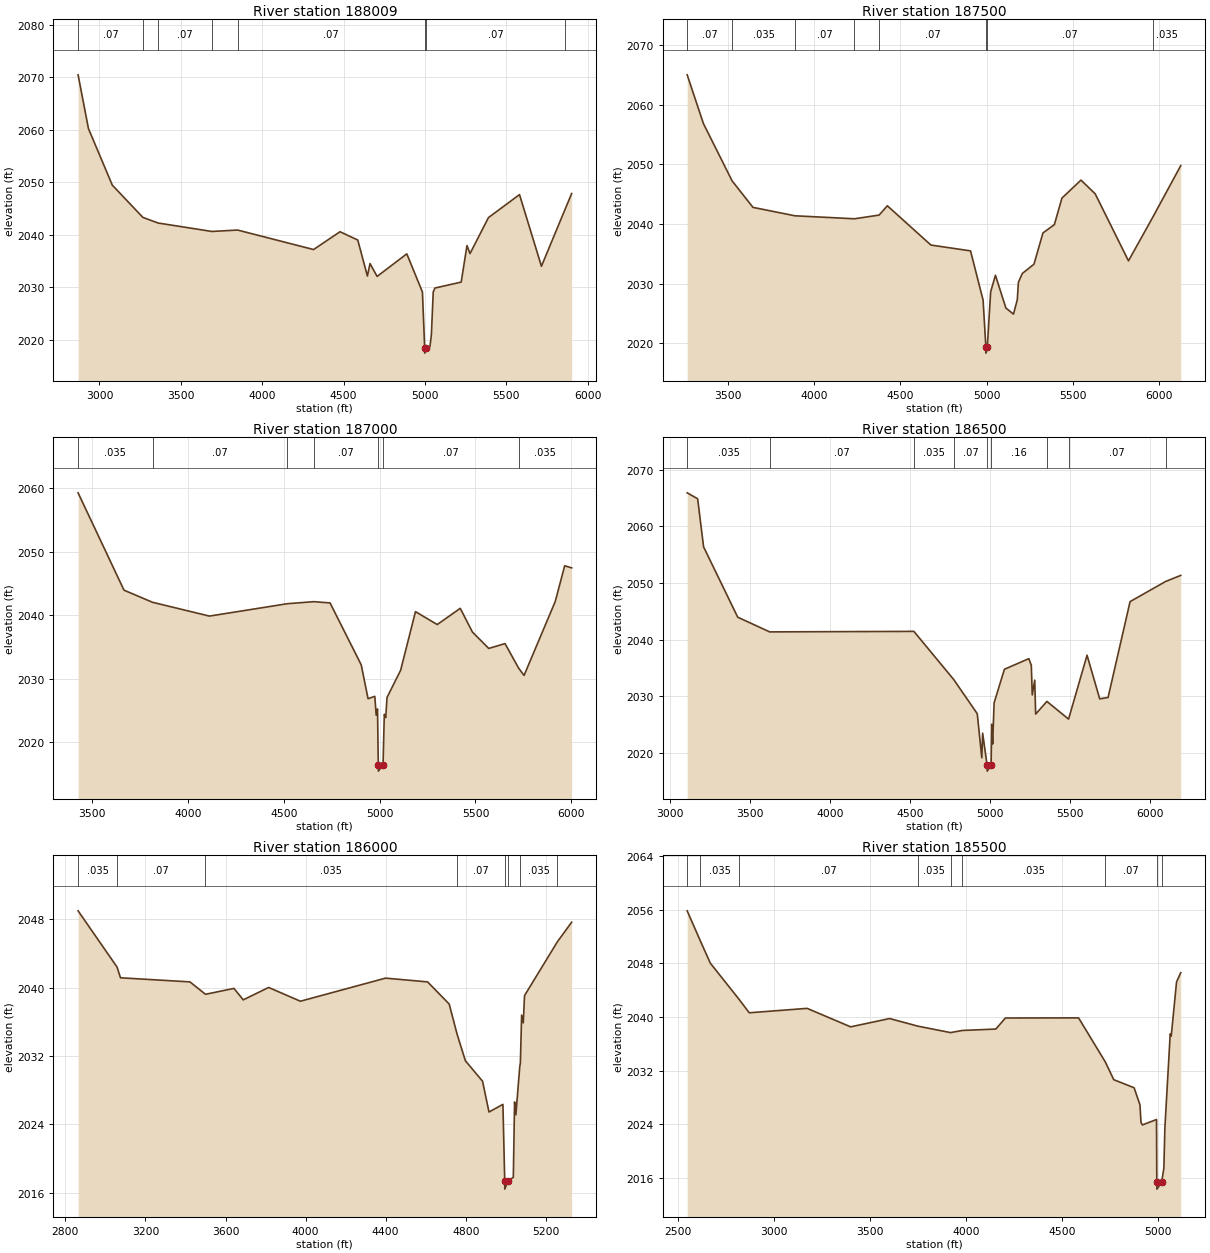
Type RM Length L Ch R = 1,188009,509,509,509
BEGIN DESCRIPTION:
Sweetwater Creek 375.0
END DESCRIPTION:
XS GIS Cut Line= 5
      1394610.21      6859850.66      1395583.17      6858094.92
      1395877.64      6858145.13      1396013.63      6858198.13
      1396530.31      6857934.56
#Sta/Elev= 30
  2868.8 2070.44  2932.5 2060.20  3079.0 2049.44  3266.8 2043.30  3360.2 2042.23
  3691.0 2040.62  3848.5 2040.89  4315.3 2037.18  4477.9 2040.57  4586.8 2038.99
  4646.1 2032.14  4662.2 2034.51  4705.7 2032.06  4888.1 2036.36  4984.1 2029.10
  4997.9 2018.46  4998.0 2017.46  5006.1 2018.46  5030.1 2018.68  5039.2 2021.02
  5050.4 2029.08  5060.6 2029.85  5222.2 2030.98  5257.8 2037.93  5276.5 2036.41
  5389.7 2043.26  5580.5 2047.64  5715.2 2034.00  5862.4 2044.98  5900.8 2047.84
#Mann=8,-1,0
  2868.8    0.07       0  3266.8   0.035       0  3360.2    0.07       0
  3691.0   0.035       0  3848.5    0.07       0  4997.9    0.07       0
  5006.1    0.07       0  5862.4   0.035       0
Bank Sta=4997.9,5006.1
Exp/Cntr=0.3,0.1

Type RM Length L Ch R = 1,187500,500,500,500
BEGIN DESCRIPTION:
Sweetwater Creek 374.0
END DESCRIPTION:
XS GIS Cut Line= 4
      1394653.01      6859946.86      1395499.30      6858664.36
      1395661.44      6858545.16      1396659.81      6858022.94
#Sta/Elev= 30
  3262.2 2064.98  3356.7 2056.80  3523.0 2047.21  3644.2 2042.77  3887.5 2041.36
  4233.2 2040.86  4376.1 2041.48  4423.9 2043.04  4676.8 2036.46  4906.8 2035.48
  4979.6 2027.23  4995.8 2019.35  4995.9 2018.35  5004.0 2019.35  5023.6 2028.63
  5051.3 2031.40  5111.9 2025.91  5156.0 2024.89  5178.1 2027.30  5184.6 2030.21
  5207.2 2031.69  5274.9 2033.25  5327.0 2038.48  5393.2 2039.88  5437.3 2044.33
  5547.7 2047.34  5630.4 2045.04  5823.4 2033.81  5964.0 2041.10  6126.7 2049.76
#Mann=8,-1,0
  3262.2    0.07       0  3523.0   0.035       0  3887.5    0.07       0
  4233.2   0.035       0  4376.1    0.07       0  4995.8    0.07       0
  5004.0    0.07       0  5964.0   0.035       0
Bank Sta=4995.8,5004
Exp/Cntr=0.3,0.1

Type RM Length L Ch R = 1,187000,500,500,500
BEGIN DESCRIPTION:
Sweetwater Creek 373.0
END DESCRIPTION:
XS GIS Cut Line= 3
      1394712.56      6859994.29      1395854.94      6858912.23
      1396534.96      6858176.72
#Sta/Elev= 30
  3426.5 2059.24  3666.0 2043.92  3815.1 2042.01  4111.8 2039.84  4518.8 2041.79
  4657.1 2042.11  4741.2 2041.91  4903.8 2032.17  4939.4 2026.84  4974.6 2027.21
  4981.9 2024.24  4988.8 2025.23  4992.9 2016.44  4993.3 2015.44  5017.6 2016.44
  5024.2 2024.38  5031.6 2023.87  5038.4 2027.03  5109.2 2031.30  5186.9 2040.54
  5300.3 2038.51  5420.5 2041.06  5484.0 2037.33  5569.1 2034.75  5654.1 2035.51
  5724.9 2031.66  5753.4 2030.50  5916.1 2042.14  5965.4 2047.76  6001.7 2047.43
#Mann=7,-1,0
  3426.5   0.035       0  3815.1    0.07       0  4518.8   0.035       0
  4657.1    0.07       0  4992.9    0.07       0  5017.6    0.07       0
  5724.9   0.035       0
Bank Sta=4992.9,5017.6
Exp/Cntr=0.3,0.1

Type RM Length L Ch R = 1,186500,500,500,500
BEGIN DESCRIPTION:
Sweetwater Creek 372.0
END DESCRIPTION:
XS GIS Cut Line= 4
      1394631.65      6860064.96      1396113.55      6859200.68
      1396163.21      6859029.56      1396784.90      6858012.17
#Sta/Elev= 30
  3106.3 2065.92  3171.8 2064.87  3209.0 2056.38  3422.4 2043.97  3622.3 2041.38
  4523.9 2041.47  4772.9 2032.97  4920.1 2026.94  4948.5 2019.16  4953.7 2023.51
  4981.9 2017.81  4982.3 2016.81  5006.6 2017.81  5010.4 2025.10  5016.2 2021.59
  5025.3 2028.84  5089.7 2034.78  5242.6 2036.66  5258.1 2035.46  5263.9 2030.26
  5279.4 2032.87  5285.2 2026.88  5355.6 2029.11  5491.0 2025.99  5606.5 2037.26
  5685.8 2029.56  5738.0 2029.81  5875.5 2046.72  6098.6 2050.29  6192.3 2051.35
#Mann=9,-1,0
  3106.3   0.035       0  3622.3    0.07       0  4523.9   0.035       0
  4772.9    0.07       0  4981.9    0.07       0  5006.6    0.16       0
  5355.6   0.035       0  5491.0    0.07       0  6098.6   0.035       0
Bank Sta=4981.9,5006.6
Exp/Cntr=0.3,0.1

Type RM Length L Ch R = 1,186000,500,500,500
BEGIN DESCRIPTION:
Sweetwater Creek 371.0
END DESCRIPTION:
XS GIS Cut Line= 4
      1394791.70      6860152.18      1396498.50      6859387.81
      1396595.24      6859139.86      1396855.02      6858937.98
#Sta/Elev= 30
  2863.7 2048.97  3058.4 2042.39  3075.5 2041.14  3422.5 2040.66  3500.0 2039.21
  3642.2 2039.90  3688.6 2038.56  3815.5 2040.01  3974.0 2038.40  4399.5 2041.10
  4609.5 2040.66  4717.4 2038.07  4756.5 2034.57  4798.2 2031.44  4883.9 2029.05
  4916.1 2025.45  4985.7 2026.34  4994.7 2017.43  4995.0 2016.43  5011.3 2017.43
  5037.6 2017.80  5043.9 2026.62  5050.4 2025.12  5069.8 2030.76  5072.9 2031.18
  5079.2 2036.78  5087.3 2035.87  5093.7 2039.06  5258.0 2045.36  5329.0 2047.64
#Mann=8,-1,0
  2863.7   0.035       0  3058.4    0.07       0  3500.0   0.035       0
  4756.5    0.07       0  4994.7    0.07       0  5011.3    0.07       0
  5069.8   0.035       0  5258.0    0.07       0
Bank Sta=4994.7,5011.3
Exp/Cntr=0.3,0.1

Type RM Length L Ch R = 1,185500,500,500,500
BEGIN DESCRIPTION:
Sweetwater Creek 370.0
END DESCRIPTION:
XS GIS Cut Line= 3
      1394688.04      6860264.83      1396989.97      6859422.50
      1397105.00      6859388.00
#Sta/Elev= 30
  2548.8 2055.86  2617.7 2051.35  2669.3 2048.05  2818.3 2042.67  2872.3 2040.63
  3173.8 2041.29  3400.4 2038.53  3603.4 2039.77  3751.2 2038.63  3921.0 2037.67
  3982.1 2037.99  4156.7 2038.20  4206.7 2039.85  4587.9 2039.87  4727.4 2033.28
  4771.1 2030.64  4877.2 2029.43  4907.7 2026.87  4913.0 2024.26  4920.2 2023.88
  4994.0 2024.69  4995.4 2015.29  4995.9 2014.29  5020.3 2015.29  5032.2 2017.42
  5037.4 2023.37  5065.3 2037.47  5070.5 2037.13  5098.3 2045.24  5120.1 2046.62
#Mann=9,-1,0
  2548.8    0.07       0  2617.7   0.035       0  2818.3    0.07       0
  3751.2   0.035       0  3921.0    0.07       0  3982.1   0.035       0
  4727.4    0.07       0  4995.4    0.07       0  5020.3    0.07       0
Bank Sta=4995.4,5020.3
Exp/Cntr=0.3,0.1