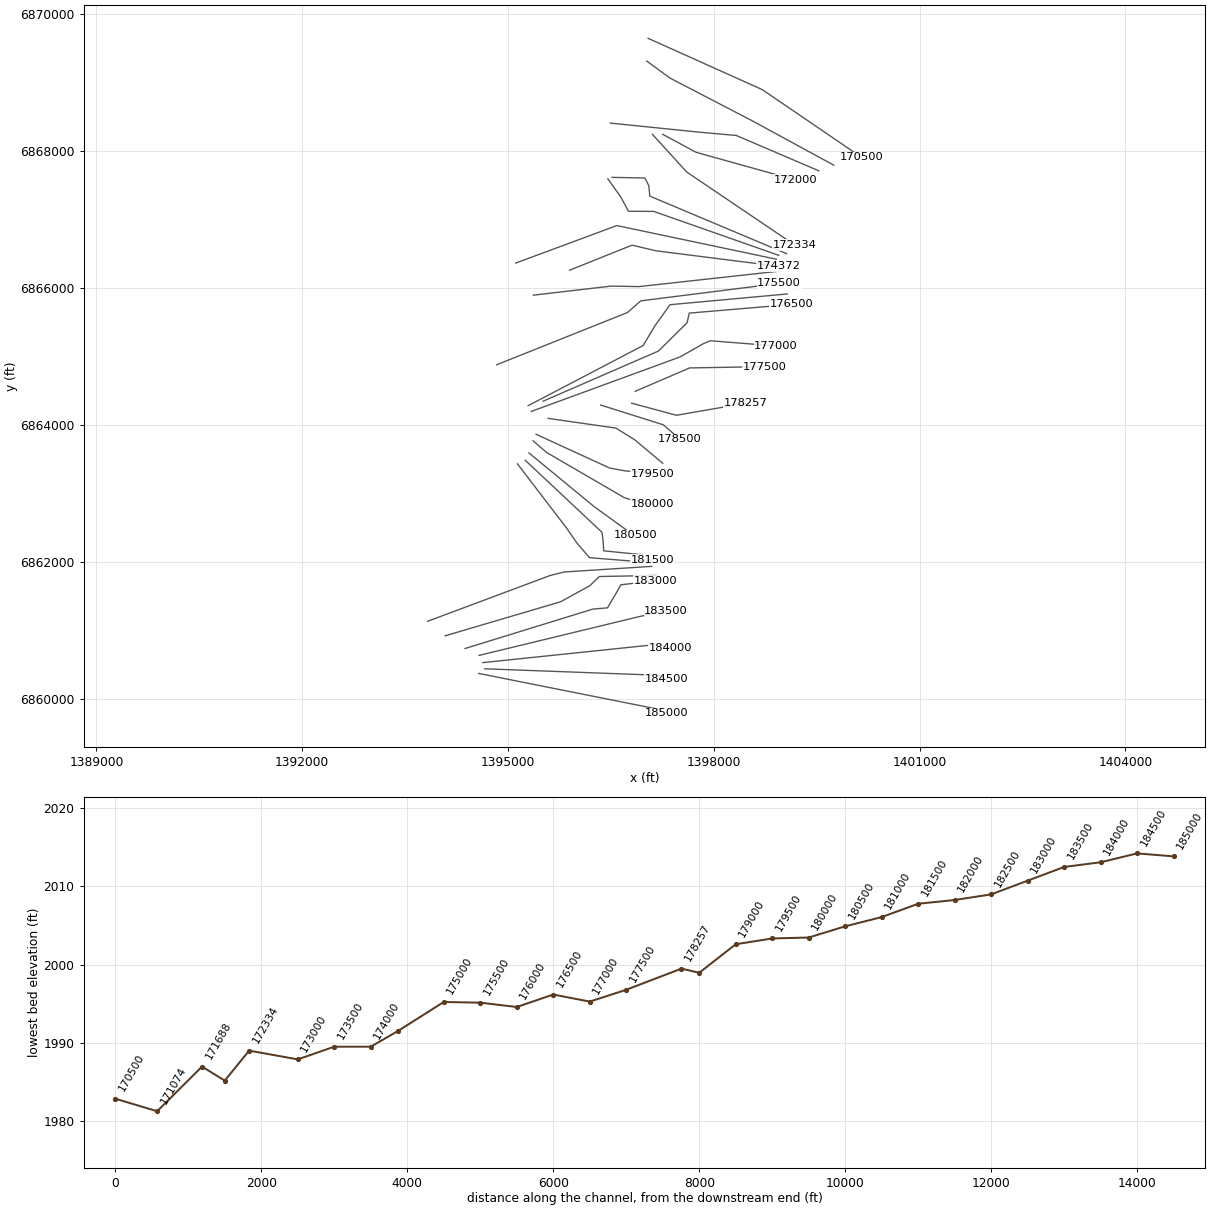
HEC-RAS study Sweetwater Creek.prj: Sweetwater Creek Base Level Engineering

--- Sweetwater Creek.g01 (geometry) --- (continued)

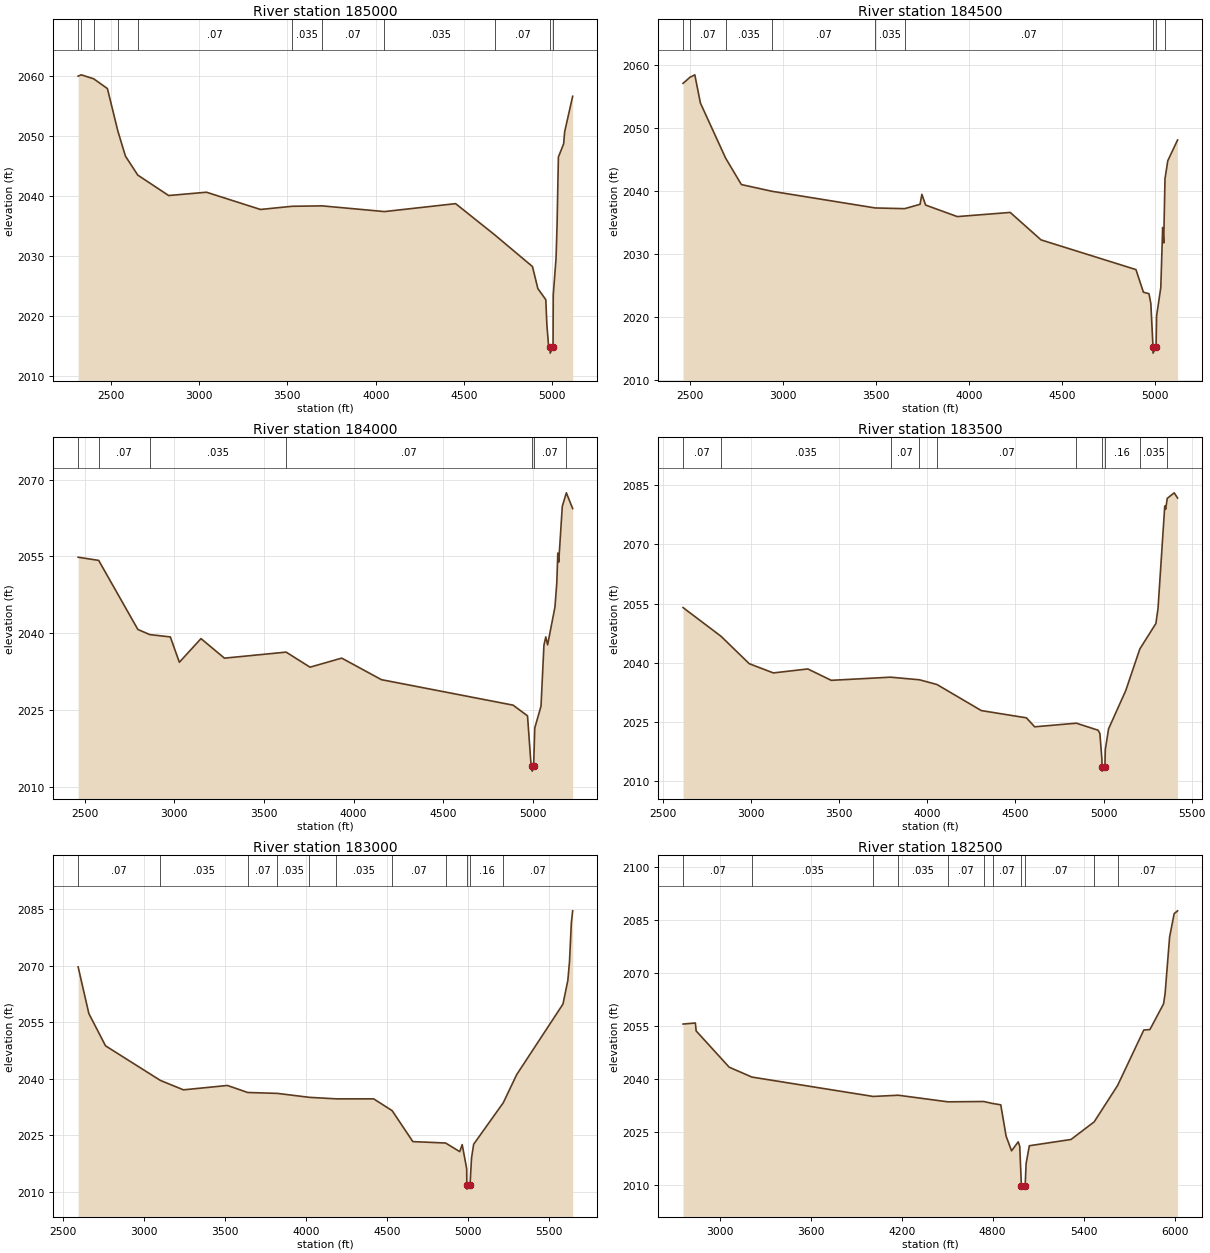
Type RM Length L Ch R = 1,185000,500,500,500
BEGIN DESCRIPTION:
Sweetwater Creek 369.0
END DESCRIPTION:
XS GIS Cut Line= 3
      1394572.42      6860370.79      1397205.34      6859845.52
      1397305.02      6859787.99
#Sta/Elev= 30
  2315.2 2059.91  2332.7 2060.13  2403.2 2059.47  2481.0 2057.84  2540.2 2050.76
  2583.0 2046.60  2652.9 2043.44  2827.7 2040.04  3041.8 2040.59  3347.7 2037.72
  3526.3 2038.25  3696.5 2038.32  4049.3 2037.37  4452.4 2038.69  4675.3 2033.46
  4887.5 2028.22  4918.1 2024.55  4962.9 2022.71  4969.1 2018.55  4979.3 2014.81
  4987.6 2014.81  4987.9 2013.81  5004.1 2014.81  5005.2 2023.49  5021.0 2029.61
  5026.8 2035.17  5034.3 2046.45  5064.1 2048.65  5069.9 2050.67  5115.1 2056.56
#Mann=11,-1,0
  2315.2    0.07       0  2332.7   0.035       0  2403.2    0.07       0
  2540.2   0.035       0  2652.9    0.07       0  3526.3   0.035       0
  3696.5    0.07       0  4049.3   0.035       0  4675.3    0.07       0
  4987.6    0.07       0  5004.1    0.07       0
Bank Sta=4987.6,5004.1
Exp/Cntr=0.3,0.1

Type RM Length L Ch R = 1,184500,500,500,500
BEGIN DESCRIPTION:
Sweetwater Creek 368.0
END DESCRIPTION:
XS GIS Cut Line= 3
      1394661.75      6860438.46      1397197.29      6860344.00
      1397305.00      6860288.00
#Sta/Elev= 30
  2462.7 2057.04  2499.4 2058.00  2526.0 2058.40  2556.0 2053.92  2691.4 2045.18
  2776.2 2040.97  2940.7 2039.90  3496.3 2037.25  3653.9 2037.14  3736.8 2037.83
  3746.8 2039.41  3766.9 2037.71  3937.0 2035.88  4221.6 2036.54  4387.3 2032.18
  4897.6 2027.46  4937.7 2023.87  4967.7 2023.63  4977.7 2022.07  4989.3 2015.19
  4989.6 2014.19  5005.8 2015.19  5008.7 2020.13  5031.2 2024.60  5041.2 2034.15
  5046.8 2031.70  5053.8 2041.93  5055.5 2042.23  5068.9 2044.76  5121.4 2048.05
#Mann=9,-1,0
  2462.7   0.035       0  2499.4    0.07       0  2691.4   0.035       0
  2940.7    0.07       0  3496.3   0.035       0  3653.9    0.07       0
  4989.3    0.07       0  5005.8    0.07       0  5055.5    0.07       0
Bank Sta=4989.3,5005.8
Exp/Cntr=0.3,0.1

Type RM Length L Ch R = 1,184000,500,500,500
BEGIN DESCRIPTION:
Sweetwater Creek 367.0
END DESCRIPTION:
XS GIS Cut Line= 3
      1394633.99      6860529.00      1397155.81      6860792.07
      1397371.49      6860745.74
#Sta/Elev= 30
  2464.5 2054.85  2579.0 2054.23  2797.3 2040.74  2864.0 2039.73  2978.3 2039.28
  3028.6 2034.33  3149.2 2038.95  3279.9 2035.13  3623.7 2036.31  3756.8 2033.37
  3933.4 2035.14  4154.6 2030.93  4888.6 2025.95  4969.0 2023.86  4989.1 2014.06
  4994.8 2014.06  4994.9 2013.06  5003.1 2014.06  5009.4 2021.49  5044.2 2025.75
  5060.5 2037.68  5070.8 2039.28  5081.0 2037.73  5121.9 2045.13  5132.1 2049.84
  5137.8 2055.66  5142.9 2053.91  5162.8 2064.80  5185.5 2067.43  5220.6 2064.36
#Mann=7,-1,0
  2464.5   0.035       0  2579.0    0.07       0  2864.0   0.035       0
  3623.7    0.07       0  4994.8    0.07       0  5003.1    0.07       0
  5185.5   0.035       0
Bank Sta=4994.8,5003.1
Exp/Cntr=0.3,0.1

Type RM Length L Ch R = 1,183500,500,500,500
BEGIN DESCRIPTION:
Sweetwater Creek 366.0
END DESCRIPTION:
XS GIS Cut Line= 3
      1394577.12      6860633.89      1396895.03      6861196.01
      1397305.04      6861288.01
#Sta/Elev= 30
  2614.9 2053.98  2830.1 2046.70  2990.6 2039.73  3127.2 2037.39  3322.7 2038.40
  3455.5 2035.51  3792.2 2036.31  3956.0 2035.65  4055.3 2034.45  4306.9 2027.83
  4562.8 2025.99  4609.7 2023.71  4845.9 2024.63  4969.1 2022.85  4979.4 2022.03
  4991.0 2015.46  4991.2 2013.46  4991.5 2012.46  5007.8 2013.46  5010.2 2017.92
  5028.8 2023.20  5125.7 2032.85  5206.2 2043.48  5297.2 2049.94  5309.3 2053.76
  5347.5 2079.77  5352.6 2078.96  5361.6 2081.70  5401.1 2083.11  5420.2 2081.79
#Mann=10,-1,0
  2614.9    0.07       0  2830.1   0.035       0  3792.2    0.07       0
  3956.0   0.035       0  4055.3    0.07       0  4845.9    0.16       0
  4991.2    0.07       0  5007.8    0.16       0  5206.2   0.035       0
  5361.6    0.07       0
Bank Sta=4991.2,5007.8
Exp/Cntr=0.3,0.1

Type RM Length L Ch R = 1,183000,500,500,500
BEGIN DESCRIPTION:
Sweetwater Creek 365.0
END DESCRIPTION:
XS GIS Cut Line= 6
      1394373.37      6860734.46      1396234.93      6861309.42
      1396450.57      6861328.01      1396574.50      6861538.58
      1396644.37      6861663.98      1397144.49      6861724.42
#Sta/Elev= 30
  2590.9 2069.68  2657.2 2057.30  2760.3 2048.74  3098.8 2039.57  3241.5 2037.06
  3513.6 2038.22  3638.6 2036.36  3821.7 2036.12  4020.6 2035.07  4185.6 2034.67
  4417.4 2034.67  4531.7 2031.53  4659.7 2023.32  4862.0 2022.95  4949.4 2020.66
  4964.5 2022.52  4992.3 2016.14  4993.3 2011.71  4993.6 2010.71  5009.9 2011.71
  5013.9 2012.54  5022.2 2018.97  5035.6 2022.64  5218.5 2033.64  5301.2 2041.09
  5587.4 2059.82  5617.6 2066.12  5627.7 2071.08  5639.1 2081.39  5647.3 2084.57
#Mann=11,-1,0
  2590.9    0.07       0  3098.8   0.035       0  3638.6    0.07       0
  3821.7   0.035       0  4020.6    0.07       0  4185.6   0.035       0
  4531.7    0.07       0  4862.0    0.16       0  4993.3    0.07       0
  5009.9    0.16       0  5218.5    0.07       0
Bank Sta=4993.3,5009.9
Exp/Cntr=0.3,0.1

Type RM Length L Ch R = 1,182500,500,500,500
BEGIN DESCRIPTION:
Sweetwater Creek 364.0
END DESCRIPTION:
XS GIS Cut Line= 5
      1394083.13      6860919.70      1395765.21      6861416.31
      1396192.56      6861651.20      1396330.95      6861785.22
      1397157.56      6861800.38
#Sta/Elev= 30
  2758.5 2055.57  2839.7 2055.87  2844.9 2053.63  3062.8 2043.39  3212.5 2040.60
  4012.1 2035.13  4177.4 2035.47  4505.4 2033.61  4741.0 2033.70  4801.0 2033.13
  4853.6 2032.76  4888.7 2023.93  4924.7 2019.78  4968.6 2022.31  4978.6 2021.04
  4989.5 2009.96  4990.0 2008.96  5014.4 2009.96  5020.6 2016.18  5042.0 2021.21
  5316.7 2022.98  5469.4 2027.95  5624.1 2038.24  5796.8 2053.89  5836.8 2054.01
  5926.8 2061.25  5936.8 2064.03  5966.8 2080.12  5996.8 2086.74  6019.4 2087.54
#Mann=11,-1,0
  2758.5    0.07       0  3212.5   0.035       0  4012.1    0.07       0
  4177.4   0.035       0  4505.4    0.07       0  4741.0   0.035       0
  4801.0    0.07       0  4989.5    0.07       0  5014.4    0.07       0
  5469.4    0.16       0  5624.1    0.07       0
Bank Sta=4989.5,5014.4
Exp/Cntr=0.3,0.1

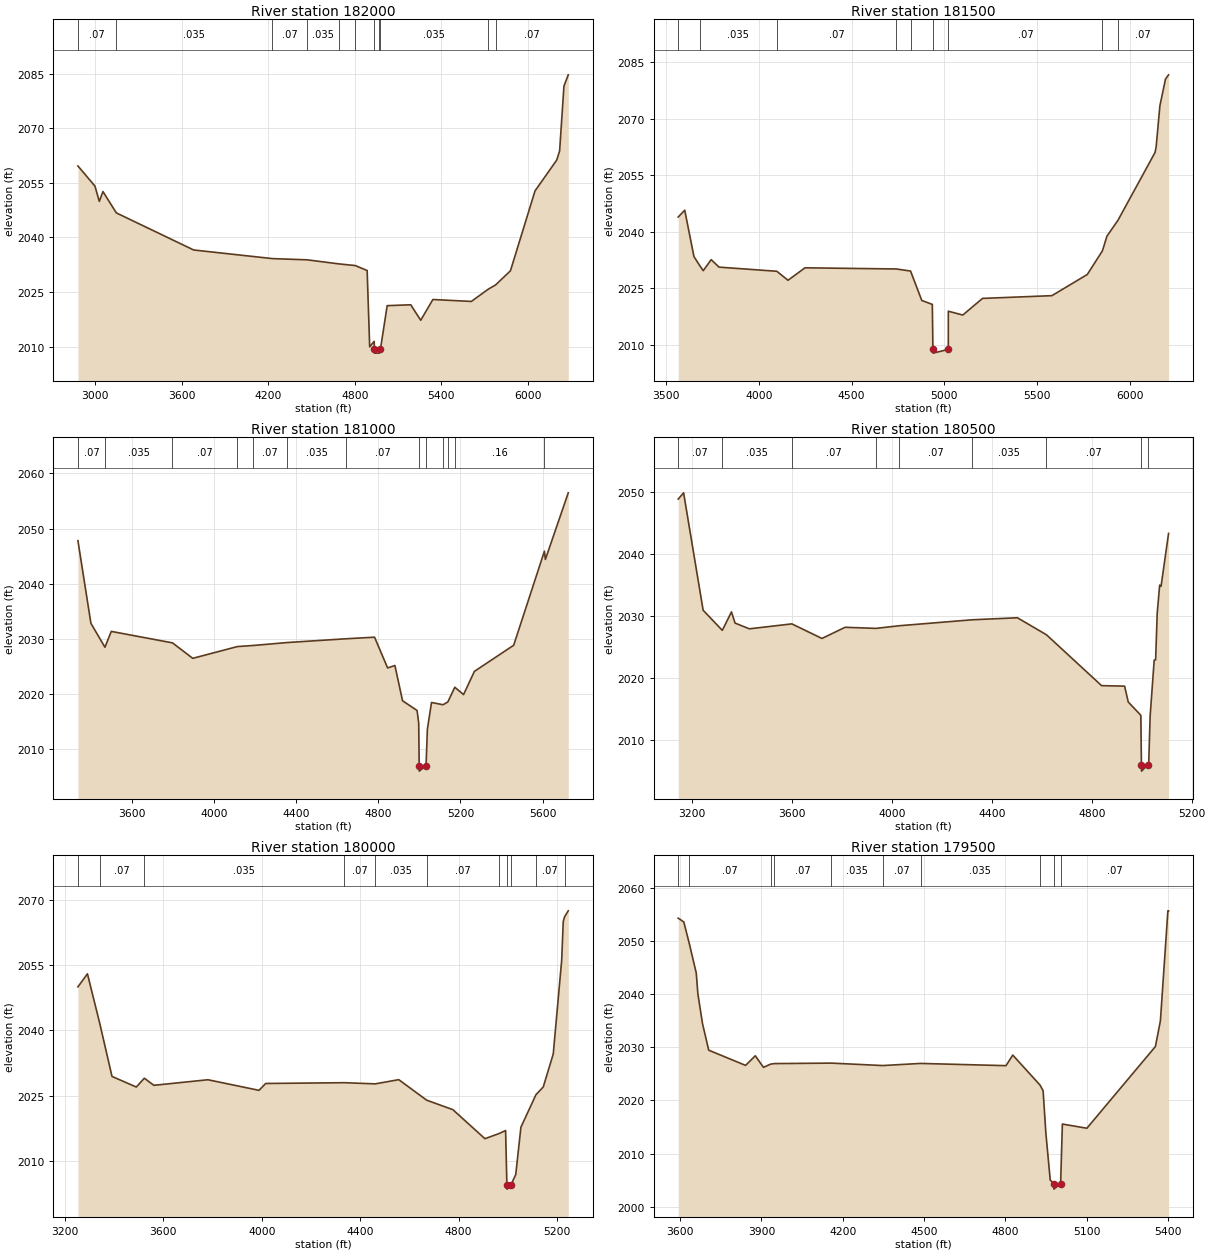
Type RM Length L Ch R = 1,182000,500,500,500
BEGIN DESCRIPTION:
Sweetwater Creek 363.0
END DESCRIPTION:
XS GIS Cut Line= 4
      1393828.60      6861132.02      1395613.47      6861799.94
      1395818.71      6861851.23      1397094.79      6861933.04
#Sta/Elev= 30
  2882.7 2059.62  3000.6 2054.09  3030.9 2049.89  3055.9 2052.60  3148.9 2046.73
  3684.7 2036.55  4229.5 2034.19  4471.1 2033.85  4689.5 2032.74  4803.6 2032.28
  4885.8 2030.92  4903.4 2009.97  4934.3 2011.47  4936.1 2009.24  4936.9 2008.24
  4970.8 2008.24  4977.6 2009.24  5024.5 2021.27  5187.8 2021.51  5256.8 2017.26
  5341.1 2022.96  5607.5 2022.43  5724.4 2025.79  5775.0 2026.95  5878.1 2030.83
  6048.4 2052.77  6198.7 2061.23  6218.8 2063.74  6248.8 2081.54  6278.7 2084.64
#Mann=11,-1,0
  2882.7    0.07       0  3148.9   0.035       0  4229.5    0.07       0
  4471.1   0.035       0  4689.5    0.07       0  4803.6   0.035       0
  4936.1    0.07       0  4970.8    0.07       0  4977.6   0.035       0
  5724.4    0.16       0  5775.0    0.07       0
Bank Sta=4936.1,4977.6
Exp/Cntr=0.3,0.1

Type RM Length L Ch R = 1,181500,500,500,500
BEGIN DESCRIPTION:
Sweetwater Creek 362.0
END DESCRIPTION:
XS GIS Cut Line= 6
      1395137.42      6863429.09      1395857.59      6862486.53
      1395998.32      6862281.35      1396187.56      6862059.92
      1396850.04      6862006.66      1397101.48      6862029.78
#Sta/Elev= 30
  3565.0 2043.93  3600.0 2045.74  3649.9 2033.41  3681.6 2030.97  3699.8 2029.67
  3742.6 2032.60  3785.0 2030.61  4096.5 2029.51  4156.9 2027.12  4248.4 2030.43
  4740.9 2030.12  4817.5 2029.57  4878.0 2021.75  4934.8 2020.71  4938.0 2008.76
  4939.5 2007.76  5021.0 2008.76  5021.1 2018.90  5099.0 2017.88  5205.5 2022.30
  5579.6 2023.03  5770.3 2028.66  5851.8 2034.94  5876.2 2038.84  5935.4 2043.04
  6135.5 2061.08  6141.6 2062.63  6161.7 2073.50  6191.8 2080.58  6208.4 2081.71
#Mann=9,-1,0
  3565.0    0.07       0  3681.6   0.035       0  4096.5    0.07       0
  4740.9   0.035       0  4817.5    0.07       0  4938.0    0.07       0
  5021.0    0.07       0  5851.8    0.16       0  5935.4    0.07       0
Bank Sta=4938,5021
Exp/Cntr=0.3,0.1

Type RM Length L Ch R = 1,181000,500,500,500
BEGIN DESCRIPTION:
Sweetwater Creek 361.0
END DESCRIPTION:
XS GIS Cut Line= 5
      1395249.93      6863482.50      1396369.52      6862430.57
      1396386.18      6862307.23      1396394.81      6862160.15
      1396969.09      6862101.53
#Sta/Elev= 30
  3339.3 2047.82  3402.5 2032.84  3470.7 2028.51  3501.6 2031.38  3799.3 2029.30
  3897.8 2026.50  4115.2 2028.63  4193.0 2028.83  4357.0 2029.36  4642.3 2030.04
  4782.3 2030.33  4845.8 2024.76  4881.2 2025.20  4918.5 2018.81  4989.1 2017.05
  4997.1 2014.74  4999.4 2007.06  5000.0 2006.06  5032.8 2007.06  5039.3 2013.67
  5059.3 2018.50  5115.2 2018.09  5138.7 2018.59  5172.7 2021.26  5215.3 2019.93
  5268.1 2024.14  5459.1 2028.87  5608.6 2045.92  5613.3 2044.42  5724.6 2056.49
#Mann=13,-1,0
  3339.3    0.07       0  3470.7   0.035       0  3799.3    0.07       0
  4115.2   0.035       0  4193.0    0.07       0  4357.0   0.035       0
  4642.3    0.07       0  4999.4    0.07       0  5032.8    0.07       0
  5115.2    0.16       0  5138.7    0.07       0  5172.7    0.16       0
  5608.6    0.07       0
Bank Sta=4999.4,5032.8
Exp/Cntr=0.3,0.1

Type RM Length L Ch R = 1,180500,500,500,500
BEGIN DESCRIPTION:
Sweetwater Creek 360.0
END DESCRIPTION:
XS GIS Cut Line= 4
      1395305.00      6863588.00      1396253.59      6862806.79
      1396760.59      6862439.04      1396854.98      6862388.01
#Sta/Elev= 30
  3144.8 2048.93  3166.3 2049.94  3244.5 2030.93  3321.2 2027.67  3357.9 2030.66
  3372.2 2028.85  3429.6 2027.92  3599.6 2028.72  3720.1 2026.36  3812.7 2028.17
  3935.9 2027.99  4029.7 2028.42  4319.9 2029.38  4502.2 2029.71  4618.5 2026.96
  4839.3 2018.72  4931.3 2018.64  4946.0 2016.07  4996.3 2013.92  4998.7 2005.88
  4999.2 2004.88  5023.7 2005.88  5027.8 2006.03  5033.6 2013.83  5049.8 2022.86
  5055.5 2022.90  5061.9 2030.48  5071.7 2035.00  5077.3 2034.81  5107.3 2043.37
#Mann=9,-1,0
  3144.8    0.07       0  3321.2   0.035       0  3599.6    0.07       0
  3935.9   0.035       0  4029.7    0.07       0  4319.9   0.035       0
  4618.5    0.07       0  4998.7    0.07       0  5023.7    0.07       0
Bank Sta=4998.7,5023.7
Exp/Cntr=0.3,0.1

Type RM Length L Ch R = 1,180000,500,500,500
BEGIN DESCRIPTION:
Sweetwater Creek 359.0
END DESCRIPTION:
XS GIS Cut Line= 5
      1395366.42      6863764.45      1395563.03      6863594.74
      1396693.08      6862937.20      1396863.62      6862881.68
      1397105.00      6862838.00
#Sta/Elev= 30
  3253.5 2050.05  3292.1 2053.06  3342.2 2041.62  3391.9 2029.42  3490.6 2026.97
  3523.2 2029.00  3562.0 2027.37  3781.6 2028.65  3989.0 2026.21  4016.3 2027.79
  4335.8 2027.97  4461.2 2027.70  4556.8 2028.67  4670.3 2023.94  4776.6 2021.76
  4906.8 2015.07  4964.5 2016.26  4990.7 2016.96  4996.0 2004.45  4996.3 2003.45
  5012.7 2004.45  5031.9 2006.80  5053.0 2017.72  5114.1 2025.21  5143.7 2026.99
  5184.3 2034.58  5218.6 2056.21  5225.0 2065.14  5230.6 2066.22  5245.3 2067.57
#Mann=11,-1,0
  3253.5   0.035       0  3342.2    0.07       0  3523.2   0.035       0
  4335.8    0.07       0  4461.2   0.035       0  4670.3    0.07       0
  4964.5    0.16       0  4996.0    0.07       0  5012.7    0.16       0
  5114.1    0.07       0  5230.6   0.035       0
Bank Sta=4996,5012.7
Exp/Cntr=0.3,0.1

Type RM Length L Ch R = 1,179500,500,500,500
BEGIN DESCRIPTION:
Sweetwater Creek 358.0
END DESCRIPTION:
XS GIS Cut Line= 4
      1395409.25      6863860.65      1396478.84      6863368.98
      1396704.86      6863326.81      1397104.98      6863288.00
#Sta/Elev= 30
  3592.9 2054.29  3613.5 2053.57  3633.9 2049.48  3659.4 2043.98  3665.3 2040.09
  3682.4 2034.48  3705.4 2029.46  3841.4 2026.60  3877.2 2028.41  3907.4 2026.23
  3933.7 2026.84  3947.8 2026.94  4157.6 2027.03  4347.4 2026.57  4487.3 2026.97
  4802.2 2026.55  4827.2 2028.54  4927.4 2022.92  4939.1 2021.85  4949.3 2013.88
  4965.4 2005.05  4978.6 2004.33  4979.1 2003.33  5003.7 2004.33  5010.2 2015.57
  5100.6 2014.78  5353.5 2030.15  5371.9 2034.98  5399.5 2055.67  5402.0 2055.67
#Mann=10,-1,0
  3592.9   0.094       0  3633.9    0.07       0  3933.7   0.035       0
  3947.8    0.07       0  4157.6   0.035       0  4347.4    0.07       0
  4487.3   0.035       0  4927.4    0.07       0  4978.6    0.07       0
  5003.7    0.07       0
Bank Sta=4978.6,5003.7
Exp/Cntr=0.3,0.1

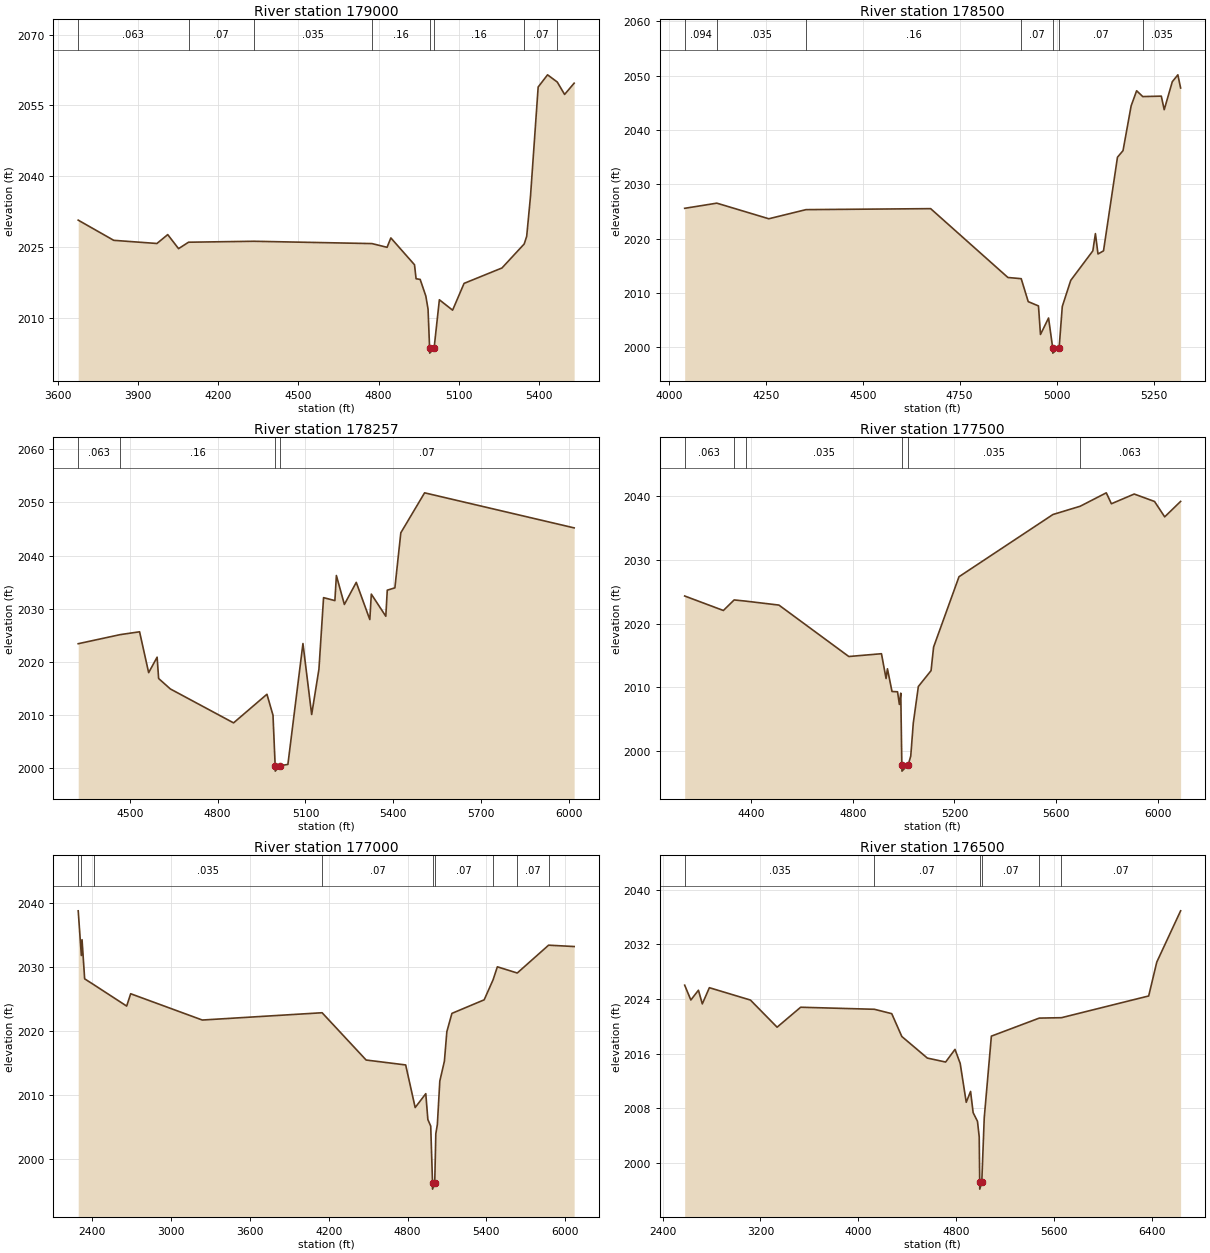
Type RM Length L Ch R = 1,179000,500,500,500
BEGIN DESCRIPTION:
Sweetwater Creek 357.0
END DESCRIPTION:
XS GIS Cut Line= 4
      1395583.56      6864093.07      1396573.21      6863950.91
      1396847.60      6863779.57      1397254.96      6863438.03
#Sta/Elev= 30
  3676.7 2030.73  3809.5 2026.46  3971.1 2025.79  4011.5 2027.67  4052.0 2024.70
  4089.4 2026.06  4333.9 2026.26  4775.3 2025.77  4831.9 2024.98  4846.0 2026.97
  4934.5 2021.29  4940.4 2018.33  4955.7 2018.19  4976.9 2014.66  4985.2 2011.88
  4991.0 2003.59  4991.3 2002.59  5007.7 2003.59  5027.5 2013.88  5077.0 2011.68
  5119.9 2017.35  5261.7 2020.61  5344.8 2025.69  5354.1 2027.31  5368.4 2035.82
  5397.0 2058.90  5432.1 2061.48  5468.4 2059.96  5495.9 2057.33  5531.6 2059.71
#Mann=8,-1,0
  3676.7   0.063       0  4089.4    0.07       0  4333.9   0.035       0
  4775.3    0.16       0  4991.0    0.07       0  5007.7    0.16       0
  5344.8    0.07       0  5468.4   0.035       0
Bank Sta=4991,5007.7
Exp/Cntr=0.3,0.1

Type RM Length L Ch R = 1,178500,243,243,243
BEGIN DESCRIPTION:
Sweetwater Creek 356.0
END DESCRIPTION:
XS GIS Cut Line= 3
      1396350.19      6864287.31      1397264.82      6863998.97
      1397505.01      6863787.99
#Sta/Elev= 30
  4041.0 2025.58  4123.9 2026.53  4257.9 2023.66  4353.9 2025.34  4675.2 2025.52
  4874.4 2012.86  4908.7 2012.64  4926.8 2008.42  4953.2 2007.63  4958.4 2002.38
  4979.2 2005.41  4989.8 1999.95  4990.1 1998.95  5006.5 1999.95  5014.6 2007.53
  5036.4 2012.33  5093.4 2017.76  5100.0 2020.93  5106.7 2017.18  5120.9 2017.76
  5156.9 2034.98  5171.2 2036.19  5192.1 2044.42  5206.3 2047.20  5222.1 2046.13
  5269.9 2046.21  5277.4 2043.72  5298.3 2048.87  5312.6 2050.13  5319.7 2047.71
#Mann=7,-1,0
  4041.0   0.094       0  4123.9   0.035       0  4353.9    0.16       0
  4908.7    0.07       0  4989.8    0.07       0  5006.5    0.07       0
  5222.1   0.035       0
Bank Sta=4989.8,5006.5
Exp/Cntr=0.3,0.1

Type RM Length L Ch R = 1,178257,757,757,757
BEGIN DESCRIPTION:
Sweetwater Creek 355.0
END DESCRIPTION:
XS GIS Cut Line= 3
      1396802.67      6864313.95      1397455.00      6864138.00
      1398458.20      6864312.48
#Sta/Elev= 30
  4323.9 2023.43  4467.5 2025.14  4533.5 2025.67  4564.5 2017.99  4593.4 2020.90
  4598.6 2016.89  4638.5 2014.93  4854.5 2008.55  4968.5 2013.93  4989.2 2009.99
  4996.6 2000.48  4996.9 1999.48  5013.3 2000.48  5040.1 2000.75  5091.5 2023.46
  5121.3 2010.12  5146.1 2018.64  5161.9 2032.09  5200.6 2031.53  5205.7 2036.25
  5233.0 2030.81  5273.6 2034.96  5319.9 2027.97  5325.0 2032.75  5374.5 2028.59
  5379.5 2033.49  5405.5 2033.93  5425.8 2044.28  5507.0 2051.79  6017.8 2045.20
#Mann=4,-1,0
  4323.9   0.063       0  4467.5    0.16       0  4996.6    0.07       0
  5013.3    0.07       0
Bank Sta=4996.6,5013.3
Exp/Cntr=0.3,0.1

Type RM Length L Ch R = 1,177500,500,500,500
BEGIN DESCRIPTION:
Sweetwater Creek 354.0
END DESCRIPTION:
XS GIS Cut Line= 3
      1396855.00      6864488.00      1397647.15      6864828.93
      1398737.68      6864847.80
#Sta/Elev= 30
  4137.6 2024.33  4290.0 2022.05  4332.4 2023.71  4378.8 2023.52  4508.8 2022.90
  4784.0 2014.81  4912.6 2015.25  4930.7 2011.35  4936.1 2012.88  4954.1 2009.31
  4975.9 2009.26  4983.2 2007.27  4988.6 2009.05  4992.8 1997.78  4993.3 1996.78
  5017.9 1997.78  5027.9 1999.14  5037.9 2004.34  5057.9 2010.10  5107.9 2012.59
  5117.9 2016.30  5217.9 2027.36  5587.9 2037.15  5695.2 2038.45  5798.0 2040.56
  5818.1 2038.84  5908.0 2040.37  5988.0 2039.20  6028.0 2036.78  6090.7 2039.21
#Mann=6,-1,0
  4137.6   0.063       0  4332.4   0.094       0  4378.8   0.035       0
  4992.8   0.035       0  5017.9   0.035       0  5695.2   0.063       0
Bank Sta=4992.8,5017.9
Exp/Cntr=0.3,0.1

Type RM Length L Ch R = 1,177000,500,500,500
BEGIN DESCRIPTION:
Sweetwater Creek 353.0
END DESCRIPTION:
XS GIS Cut Line= 5
      1395338.85      6864194.38      1397509.19      6864989.78
      1397851.09      6865184.57      1397951.20      6865225.35
      1398907.31      6865149.57
#Sta/Elev= 30
  2295.0 2038.77  2318.9 2031.79  2324.1 2034.26  2344.0 2028.14  2413.9 2027.22
  2663.6 2023.88  2694.1 2025.81  3238.8 2021.70  4150.2 2022.84  4484.9 2015.45
  4785.8 2014.68  4858.0 2008.02  4938.7 2010.19  4954.6 2006.14  4976.2 2005.13
  4990.0 1996.27  4990.3 1995.27  5006.8 1996.27  5015.0 2003.92  5026.8 2005.38
  5045.4 2012.16  5080.3 2015.27  5098.9 2019.88  5137.4 2022.74  5382.8 2024.86
  5450.8 2028.00  5483.1 2030.02  5634.5 2029.05  5872.8 2033.40  6067.2 2033.19
#Mann=9,-1,0
  2295.0   0.094       0  2318.9   0.063       0  2413.9   0.035       0
  4150.2    0.07       0  4990.0    0.07       0  5006.8    0.07       0
  5450.8   0.035       0  5634.5    0.07       0  5872.8   0.035       0
Bank Sta=4990,5006.8
Exp/Cntr=0.3,0.1

Type RM Length L Ch R = 1,176500,500,500,500
BEGIN DESCRIPTION:
Sweetwater Creek 352.0
END DESCRIPTION:
XS GIS Cut Line= 6
      1395511.71      6864343.69      1397193.52      6865075.67
      1397404.31      6865284.44      1397609.88      6865488.04
      1397641.89      6865628.99      1399129.30      6865755.18
#Sta/Elev= 30
  2579.8 2026.02  2630.3 2023.85  2692.4 2025.28  2724.1 2023.28  2781.8 2025.65
  3117.8 2023.84  3335.9 2019.87  3528.5 2022.79  4132.2 2022.49  4273.8 2021.85
  4356.4 2018.51  4565.2 2015.35  4714.7 2014.77  4791.5 2016.62  4833.9 2014.57
  4883.4 2008.88  4918.8 2010.47  4939.9 2007.36  4975.3 2006.10  4989.5 2003.84
  4993.7 1997.17  4994.0 1996.17  5010.4 1997.17  5030.7 2006.62  5089.0 2018.56
  5480.7 2021.20  5662.4 2021.26  6376.0 2024.44  6442.3 2029.40  6637.3 2036.90
#Mann=6,-1,0
  2579.8   0.035       0  4132.2    0.07       0  4993.7    0.07       0
  5010.4    0.07       0  5480.7   0.035       0  5662.4    0.07       0
Bank Sta=4993.7,5010.4
Exp/Cntr=0.3,0.1

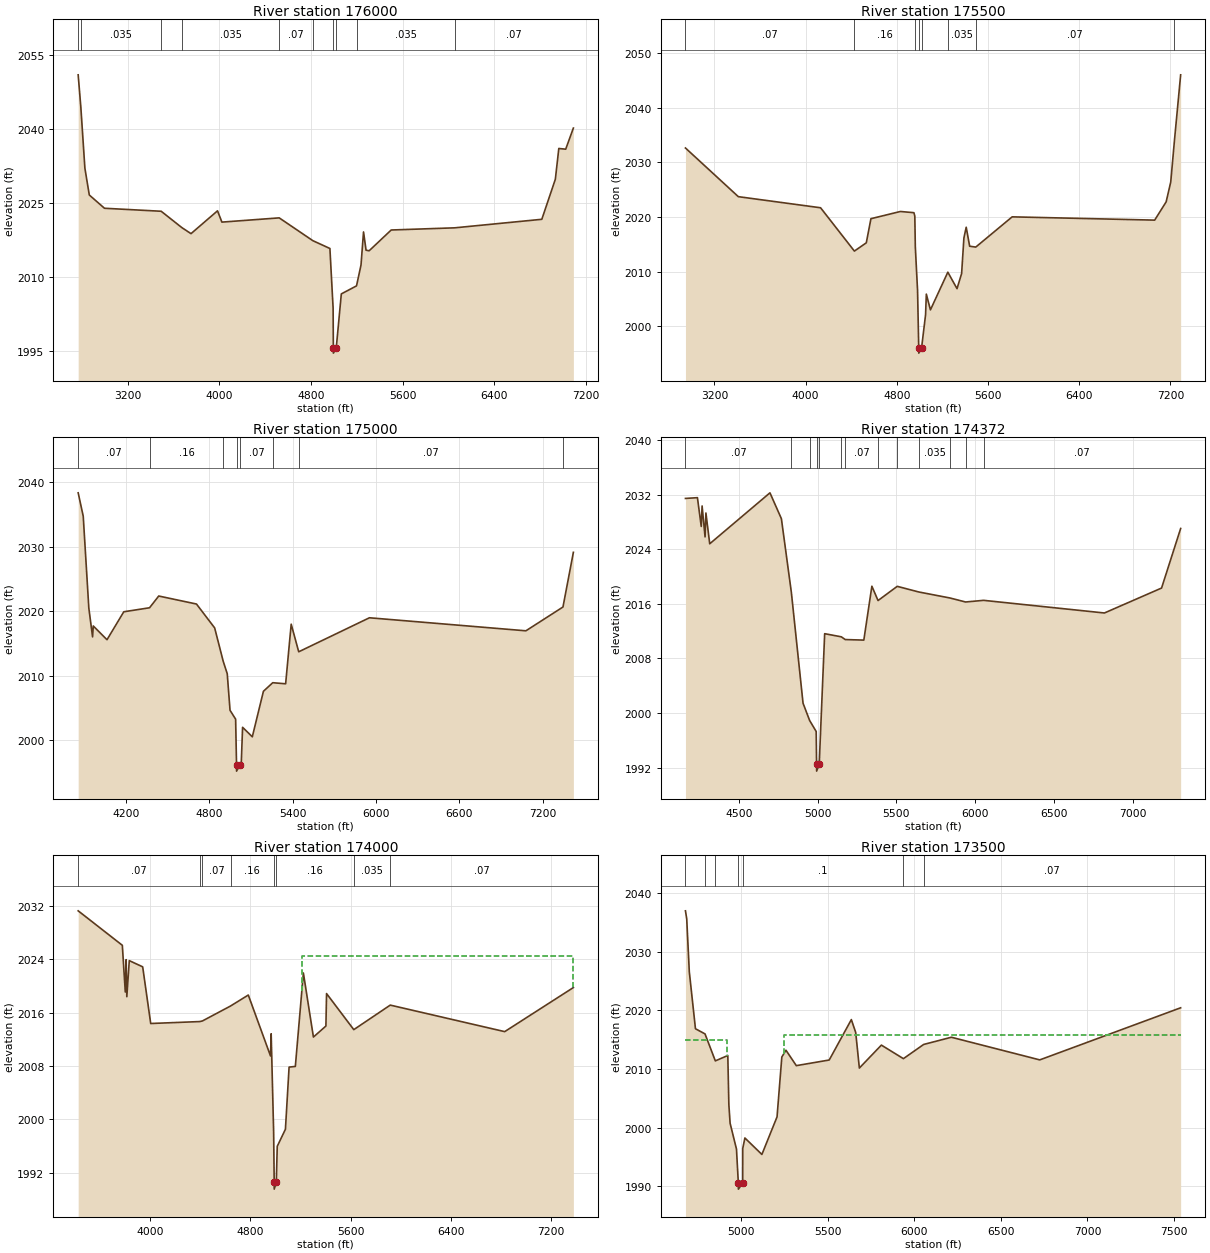
Type RM Length L Ch R = 1,176000,500,500,500
BEGIN DESCRIPTION:
Sweetwater Creek 351.0
END DESCRIPTION:
XS GIS Cut Line= 5
      1395293.35      6864278.30      1396970.19      6865156.00
      1397144.64      6865448.93      1397362.27      6865751.66
      1399071.66      6865908.40
#Sta/Elev= 30
  2766.4 2051.02  2789.6 2044.49  2825.0 2032.09  2863.5 2026.65  2995.9 2023.96
  3491.1 2023.35  3671.3 2020.04  3751.4 2018.81  3982.9 2023.44  4021.1 2021.15
  4521.4 2022.01  4814.8 2017.39  4964.0 2015.80  4992.0 2003.68  4994.0 1995.58
  4994.5 1994.58  5019.1 1995.58  5063.6 2006.59  5196.3 2008.22  5235.5 2012.45
  5257.5 2019.16  5279.6 2015.45  5306.7 2015.34  5499.1 2019.55  6053.1 2019.99
  6813.9 2021.72  6932.1 2029.85  6962.2 2036.08  7022.5 2035.94  7089.4 2040.22
#Mann=10,-1,0
  2766.4   0.063       0  2789.6   0.035       0  3491.1    0.07       0
  3671.3   0.035       0  4521.4    0.07       0  4814.8    0.16       0
  4994.0    0.07       0  5019.1    0.16       0  5196.3   0.035       0
  6053.1    0.07       0
Bank Sta=4994,5019.1
Exp/Cntr=0.3,0.1

Type RM Length L Ch R = 1,175500,500,500,500
BEGIN DESCRIPTION:
Sweetwater Creek 350.0
END DESCRIPTION:
XS GIS Cut Line= 4
      1394834.29      6864875.16      1396741.13      6865637.55
      1396934.73      6865807.69      1398951.21      6866062.85
#Sta/Elev= 30
  2946.4 2032.64  3410.3 2023.74  4131.8 2021.71  4428.2 2013.79  4532.8 2015.30
  4573.4 2019.71  4831.9 2021.03  4950.3 2020.81  4958.3 2020.21  4962.8 2014.56
  4982.5 2006.54  4992.7 1996.13  4993.2 1995.13  5017.9 1996.13  5052.7 2002.15
  5059.4 2005.92  5095.4 2003.04  5248.0 2009.93  5328.6 2006.92  5368.9 2009.68
  5389.0 2016.19  5409.2 2018.15  5439.4 2014.68  5493.0 2014.52  5812.4 2020.05
  7062.3 2019.45  7163.1 2022.79  7203.4 2026.43  7235.7 2033.97  7290.3 2046.02
#Mann=8,-1,0
  2946.4    0.07       0  4428.2    0.16       0  4962.8    0.07       0
  4992.7    0.07       0  5017.9    0.16       0  5248.0   0.035       0
  5493.0    0.07       0  7235.7   0.035       0
Bank Sta=4992.7,5017.9
Exp/Cntr=0.3,0.1

Type RM Length L Ch R = 1,175000,628,628,628
BEGIN DESCRIPTION:
Sweetwater Creek 349.0
END DESCRIPTION:
XS GIS Cut Line= 4
      1395368.83      6865890.77      1396504.94      6866023.17
      1396909.05      6866015.93      1398914.74      6866236.87
#Sta/Elev= 30
  3856.2 2038.34  3892.6 2034.72  3932.9 2020.49  3959.9 2016.02  3965.0 2017.71
  4063.8 2015.58  4184.6 2019.91  4370.1 2020.53  4436.3 2022.35  4708.1 2021.11
  4839.0 2017.41  4900.6 2012.24  4929.6 2010.31  4949.7 2004.65  4990.0 2003.27
  4996.5 1996.22  4996.9 1995.22  5021.6 1996.22  5030.1 1996.22  5040.1 2002.01
  5110.1 2000.54  5190.1 2007.59  5257.2 2008.92  5350.1 2008.75  5390.1 2017.99
  5444.3 2013.71  5953.4 2018.98  7080.2 2016.96  7347.1 2020.65  7422.0 2029.12
#Mann=8,-1,0
  3856.2    0.07       0  4370.1    0.16       0  4900.6    0.07       0
  4996.5    0.07       0  5021.6    0.07       0  5257.2   0.035       0
  5444.3    0.07       0  7347.1   0.035       0
Bank Sta=4996.5,5021.6
Exp/Cntr=0.3,0.1

Type RM Length L Ch R = 1,174372,372,372,372
BEGIN DESCRIPTION:
Sweetwater Creek 348.0
END DESCRIPTION:
XS GIS Cut Line= 4
      1395897.75      6866255.44      1396808.19      6866620.30
      1397158.67      6866537.90      1398945.14      6866311.63
#Sta/Elev= 30
  4161.7 2031.43  4237.7 2031.54  4261.9 2027.33  4267.3 2030.33  4286.1 2025.80
  4291.5 2029.30  4315.7 2024.79  4697.8 2032.25  4770.4 2028.46  4833.7 2017.66
  4907.7 2001.45  4949.6 1998.92  4991.1 1997.31  4993.6 1992.51  4993.9 1991.51
  5010.3 1992.51  5044.9 2011.63  5150.6 2011.17  5175.4 2010.77  5293.3 2010.69
  5344.4 2018.58  5383.5 2016.48  5505.2 2018.56  5643.0 2017.73  5841.1 2016.85
  5938.6 2016.27  6053.3 2016.51  6819.6 2014.66  7182.2 2018.31  7303.3 2027.03
#Mann=13,-1,0
  4161.7    0.07       0  4833.7    0.16       0  4949.6    0.07       0
  4993.6    0.07       0  5010.3    0.07       0  5150.6   0.035       0
  5175.4    0.07       0  5383.5   0.035       0  5505.2    0.07       0
  5643.0   0.035       0  5841.1    0.07       0  5938.6   0.035       0
  6053.3    0.07       0
Bank Sta=4993.6,5010.3
Exp/Cntr=0.3,0.1

Type RM Length L Ch R = 1,174000,500,500,500
BEGIN DESCRIPTION:
Sweetwater Creek 347.0
END DESCRIPTION:
XS GIS Cut Line= 3
      1395112.98      6866359.37      1396586.19      6866906.40
      1398910.69      6866415.81
#Sta/Elev= 30
  3428.5 2031.25  3780.5 2026.08  3804.0 2019.08  3810.9 2023.92  3816.2 2018.37
  3835.9 2023.78  3942.7 2022.85  4006.7 2014.35  4396.5 2014.64  4418.6 2014.73
  4642.7 2016.97  4784.6 2018.62  4961.5 2009.49  4966.8 2012.81  4986.5 1998.13
  4991.0 1990.51  4991.3 1989.51  5007.7 1990.51  5015.3 1995.93  5080.5 1998.49
  5109.7 2007.81  5159.5 2007.91  5223.6 2021.93  5303.6 2012.32  5403.2 2013.97
  5408.3 2018.84  5625.4 2013.43  5916.1 2017.11  6828.2 2013.13  7375.7 2019.74
#Mann=8,-1,0
  3428.5    0.07       0  4396.5    0.16       0  4418.6    0.07       0
  4642.7    0.16       0  4991.0    0.07       0  5007.7    0.16       0
  5625.4   0.035       0  5916.1    0.07       0
#XS Ineff=2,0
       0                 5211.50    0.00 2024.42
Permanent Ineff=
       F       F
Bank Sta=4991,5007.7
Exp/Cntr=0.3,0.1

Type RM Length L Ch R = 1,173500,500,500,500
BEGIN DESCRIPTION:
Sweetwater Creek 346.0
END DESCRIPTION:
XS GIS Cut Line= 5
      1396454.97      6867588.04      1396642.41      6867325.23
      1396755.45      6867115.49      1397124.83      6867112.76
      1398946.17      6866472.37
#Sta/Elev= 30
  4677.2 2036.95  4684.6 2035.56  4699.4 2026.58  4735.0 2016.85  4790.2 2015.97
  4849.9 2011.37  4921.9 2012.29  4928.0 2003.92  4935.2 2000.74  4972.0 1996.34
  4982.8 1990.51  4983.2 1989.51  5008.0 1990.51  5008.2 1996.43  5020.6 1998.23
  5118.8 1995.42  5206.4 2001.83  5234.0 2012.03  5257.8 2013.19  5317.8 2010.56
  5507.8 2011.52  5635.7 2018.41  5660.8 2016.22  5682.0 2010.15  5809.2 2014.06
  5936.5 2011.75  6053.4 2014.17  6213.6 2015.40  6724.3 2011.54  7538.3 2020.42
#Mann=7,-1,0
  4677.2    0.07       0  4790.2   0.035       0  4849.9    0.07       0
  4982.8    0.07       0  5008.0     0.1       0  5936.5   0.035       0
  6053.4    0.07       0
#XS Ineff=2,0
    0.00 4918.90 2014.99 5244.50    0.00 2015.74
Permanent Ineff=
       F       F
Bank Sta=4982.8,5008
Exp/Cntr=0.3,0.1

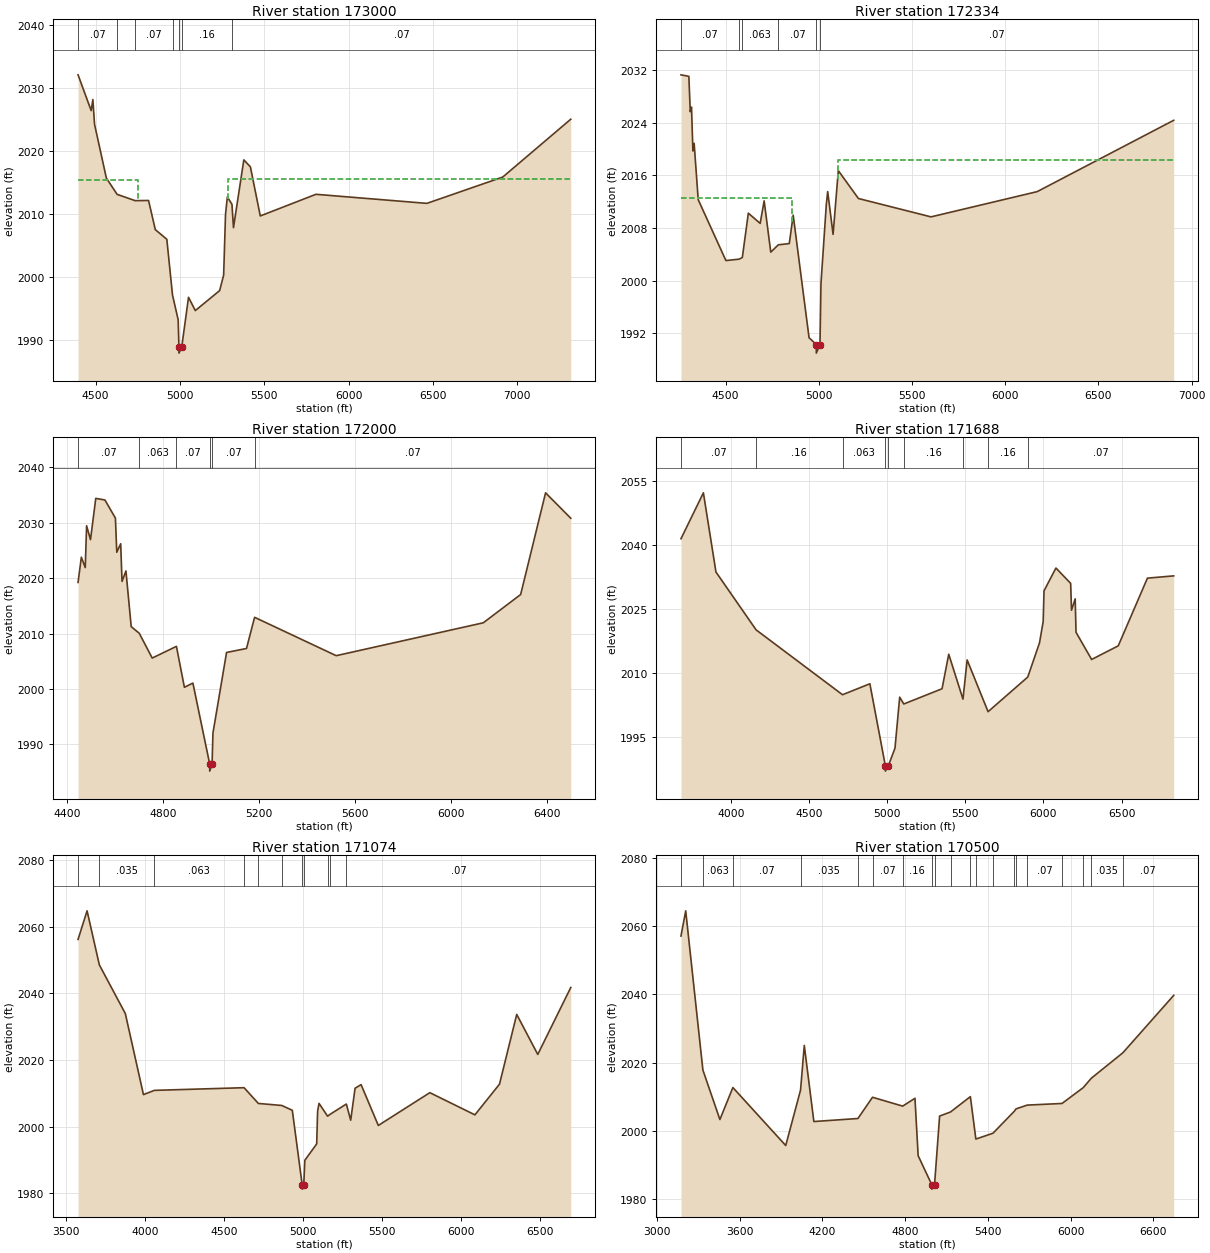
Type RM Length L Ch R = 1,173000,666,666,666
BEGIN DESCRIPTION:
Sweetwater Creek 345.0
END DESCRIPTION:
XS GIS Cut Line= 5
      1396517.19      6867609.81      1396995.72      6867600.52
      1397052.23      6867488.37      1397067.36      6867336.06
      1399061.00      6866496.17
#Sta/Elev= 30
  4395.8 2032.10  4473.6 2026.42  4483.6 2028.17  4493.6 2024.24  4563.6 2015.70
  4627.4 2013.11  4734.4 2012.11  4813.7 2012.14  4853.7 2007.51  4922.0 2005.97
  4955.7 1997.12  4989.2 1993.19  4993.7 1988.89  4994.0 1987.89  5010.5 1988.89
  5050.6 1996.76  5090.8 1994.65  5235.0 1997.82  5258.8 2000.27  5269.9 2009.93
  5280.7 2012.70  5308.0 2011.53  5317.1 2007.82  5378.4 2018.59  5417.4 2017.48
  5476.0 2009.68  5805.9 2013.12  6463.5 2011.68  6913.1 2015.86  7316.4 2025.05
#Mann=7,-1,0
  4395.8    0.07       0  4627.4   0.035       0  4734.4    0.07       0
  4955.7    0.16       0  4993.7    0.07       0  5010.5    0.16       0
  5308.0    0.07       0
#XS Ineff=2,0
    0.00 4753.30 2015.45 5287.10    0.00 2015.62
Permanent Ineff=
       F       F
Bank Sta=4993.7,5010.5
Exp/Cntr=0.3,0.1

Type RM Length L Ch R = 1,172334,334,334,334
BEGIN DESCRIPTION:
Sweetwater Creek 344.0
END DESCRIPTION:
XS GIS Cut Line= 3
      1397104.99      6868238.01      1397605.00      6867688.00
      1399178.07      6866623.53
#Sta/Elev= 30
  4261.1 2031.25  4303.3 2031.02  4310.8 2025.66  4317.5 2026.35  4325.0 2019.69
  4331.7 2020.85  4353.4 2012.31  4502.0 2003.06  4572.5 2003.27  4590.1 2003.52
  4622.3 2010.25  4685.8 2008.70  4707.1 2012.12  4742.6 2004.34  4783.4 2005.45
  4841.9 2005.64  4862.9 2009.95  4948.0 1991.35  4986.7 1990.31  4987.0 1989.01
  5006.6 1990.31  5011.9 1999.58  5040.6 2011.59  5047.9 2013.53  5076.9 2007.03
  5104.8 2016.71  5212.7 2012.48  5602.1 2009.69  6171.4 2013.52  6903.8 2024.35
#Mann=6,-1,0
  4261.1    0.07       0  4572.5   0.035       0  4590.1   0.063       0
  4783.4    0.07       0  4986.7    0.07       0  5006.6    0.07       0
#XS Ineff=2,0
    0.00 4858.00 2012.49 5101.00    0.00 2018.37
Permanent Ineff=
       F       F
Bank Sta=4986.7,5006.6
Exp/Cntr=0.3,0.1

Type RM Length L Ch R = 1,172000,312,312,312
BEGIN DESCRIPTION:
Sweetwater Creek 343.0
END DESCRIPTION:
XS GIS Cut Line= 3
      1397255.04      6868237.98      1397742.17      6867975.38
      1399186.13      6867572.54
#Sta/Elev= 30
  4446.6 2019.21  4460.3 2023.76  4476.6 2021.89  4482.2 2029.42  4498.5 2026.93
  4520.4 2034.37  4558.5 2034.08  4602.3 2030.81  4607.9 2024.65  4624.2 2026.19
  4629.8 2019.40  4646.1 2021.28  4668.0 2011.24  4701.6 2010.04  4755.5 2005.57
  4856.4 2007.68  4889.6 2000.30  4925.0 2001.06  4994.9 1986.48  4995.0 1985.18
  5004.9 1986.48  5008.5 1992.03  5065.2 2006.58  5148.3 2007.30  5182.0 2012.92
  5522.0 2006.00  6134.6 2011.93  6290.3 2017.03  6394.1 2035.37  6499.1 2030.79
#Mann=6,-1,0
  4446.6    0.07       0  4701.6   0.063       0  4856.4    0.07       0
  4994.9    0.07       0  5004.9    0.07       0  5182.0    0.07       0
Bank Sta=4994.9,5004.9
Exp/Cntr=0.3,0.1

Type RM Length L Ch R = 1,171688,614,614,614
BEGIN DESCRIPTION:
Sweetwater Creek 342.0
END DESCRIPTION:
XS GIS Cut Line= 4
      1396492.30      6868401.58      1397805.31      6868267.87
      1398327.39      6868221.19      1399531.25      6867705.30
#Sta/Elev= 30
  3680.2 2041.48  3823.6 2052.25  3904.1 2033.67  4160.9 2020.11  4714.1 2004.89
  4889.1 2007.46  4988.0 1988.27  4988.3 1986.97  5007.9 1988.27  5049.8 1992.35
  5080.0 2004.32  5106.2 2002.72  5351.1 2006.29  5393.9 2014.39  5485.1 2003.86
  5511.7 2013.05  5645.7 2000.91  5899.7 2009.04  5974.8 2017.04  5998.4 2022.05
  6003.8 2029.26  6080.0 2034.61  6174.3 2031.01  6179.7 2024.71  6203.3 2027.38
  6208.7 2019.53  6308.5 2013.16  6478.9 2016.36  6665.7 2032.24  6833.9 2032.77
#Mann=9,-1,0
  3680.2    0.07       0  4160.9    0.16       0  4714.1   0.063       0
  4988.0    0.07       0  5007.9   0.063       0  5106.2    0.16       0
  5485.1    0.07       0  5645.7    0.16       0  5899.7    0.07       0
Bank Sta=4988,5007.9
Exp/Cntr=0.3,0.1

Type RM Length L Ch R = 1,171074,574,574,574
BEGIN DESCRIPTION:
Sweetwater Creek 341.0
END DESCRIPTION:
XS GIS Cut Line= 4
      1397023.34      6869306.47      1397361.71      6869058.30
      1398555.00      6868438.00      1399748.79      6867787.97
#Sta/Elev= 30
  3573.9 2056.13  3631.1 2064.71  3709.0 2048.49  3873.6 2033.91  3988.5 2009.61
  4057.9 2010.88  4626.3 2011.68  4717.0 2006.96  4865.1 2006.35  4932.2 2004.91
  4994.9 1982.57  4995.0 1981.27  5004.9 1982.57  5011.6 1989.92  5086.9 1994.83
  5092.6 2004.62  5101.7 2006.98  5155.9 2003.14  5170.1 2003.65  5274.8 2006.78
  5302.4 2001.94  5330.2 2011.52  5368.3 2012.60  5477.5 2000.36  5804.2 2010.19
  6089.9 2003.54  6245.8 2012.74  6355.0 2033.65  6488.4 2021.66  6697.7 2041.73
#Mann=11,-1,0
  3573.9    0.07       0  3709.0   0.035       0  4057.9   0.063       0
  4626.3   0.035       0  4717.0    0.07       0  4865.1    0.16       0
  4994.9    0.07       0  5004.9    0.16       0  5155.9    0.07       0
  5170.1    0.16       0  5274.8    0.07       0
Bank Sta=4994.9,5004.9
Exp/Cntr=0.3,0.1

Type RM Length L Ch R = 1,170500,500,500,500
BEGIN DESCRIPTION:
Sweetwater Creek 340.0
END DESCRIPTION:
XS GIS Cut Line= 3
      1397042.40      6869638.60      1398707.25      6868889.81
      1400149.87      6867904.66
#Sta/Elev= 30
  3174.5 2057.08  3208.7 2064.48  3333.4 2017.78  3456.6 2003.28  3550.7 2012.66
  3933.9 1995.66  4041.3 2011.90  4068.4 2025.01  4137.9 2002.69  4457.3 2003.58
  4563.1 2009.81  4781.7 2007.21  4870.9 2009.51  4894.0 1992.67  4992.8 1984.17
  4993.1 1982.87  5012.8 1984.17  5049.6 2004.29  5129.0 2005.50  5272.6 2009.99
  5312.4 1997.55  5436.7 1999.27  5592.5 2005.76  5603.5 2006.40  5684.9 2007.51
  5937.2 2007.99  6090.8 2012.63  6149.7 2015.40  6378.2 2022.85  6746.9 2039.69
#Mann=20,-1,0
  3174.5   0.035       0  3333.4   0.063       0  3550.7    0.07       0
  4041.3   0.035       0  4457.3    0.16       0  4563.1    0.07       0
  4781.7    0.16       0  4992.8    0.07       0  5012.8    0.16       0
  5129.0    0.07       0  5272.6    0.16       0  5312.4    0.07       0
  5436.7    0.16       0  5592.5    0.07       0  5603.5   0.035       0
  5684.9    0.07       0  5937.2   0.035       0  6090.8    0.07       0
  6149.7   0.035       0  6378.2    0.07       0
Bank Sta=4992.8,5012.8
Exp/Cntr=0.3,0.1