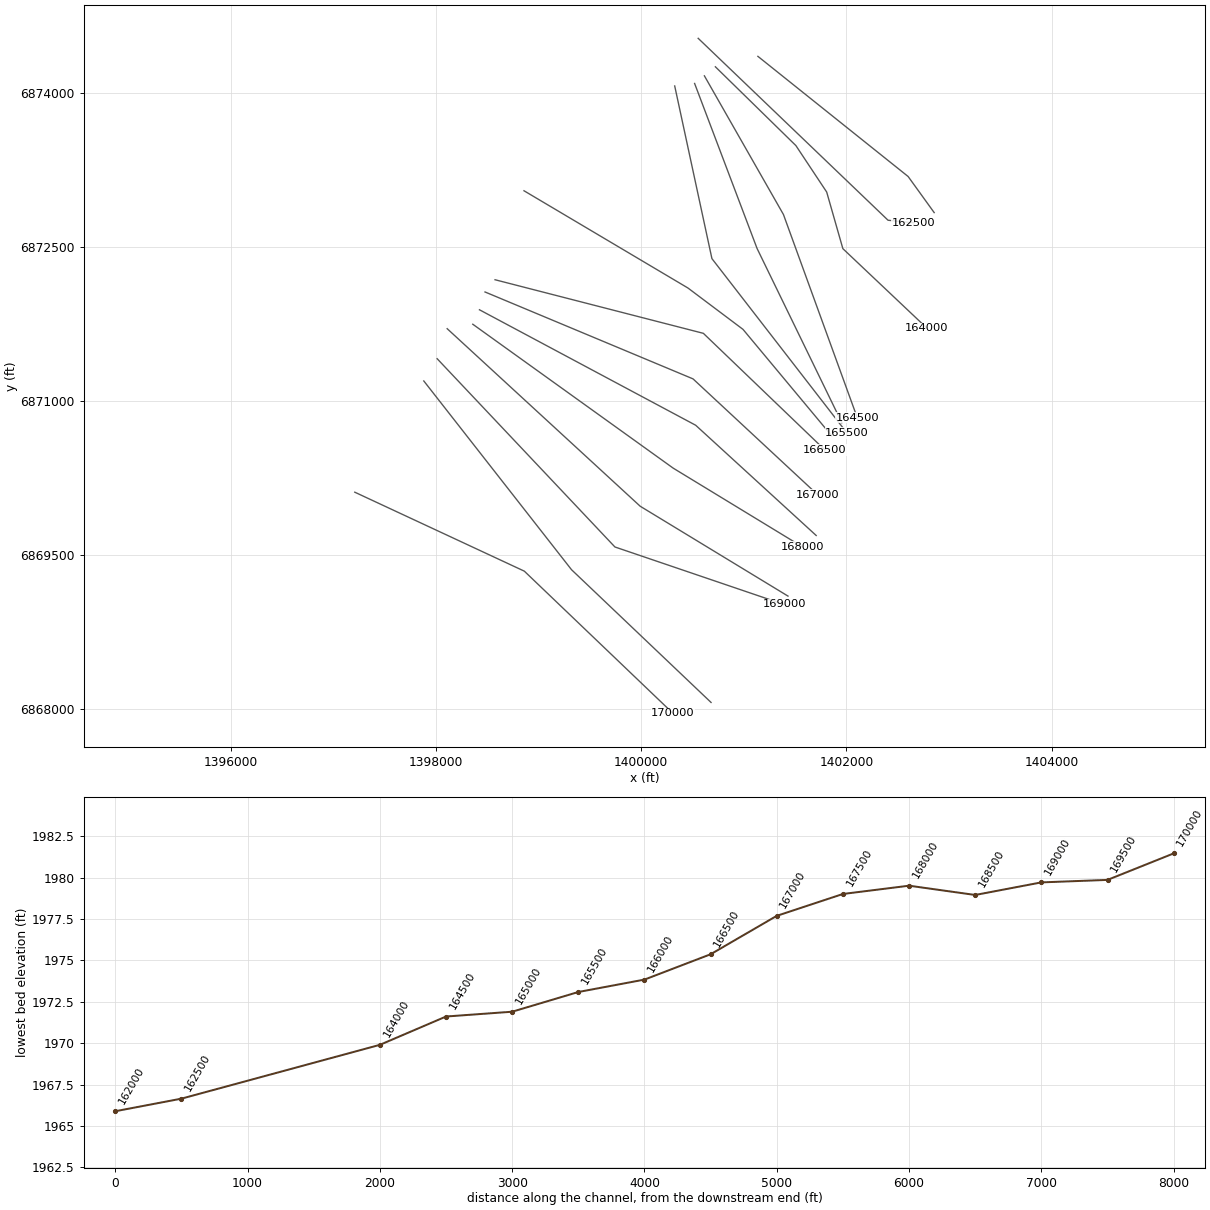
HEC-RAS study Sweetwater Creek.prj: Sweetwater Creek Base Level Engineering

--- Sweetwater Creek.g01 (geometry) --- (continued)

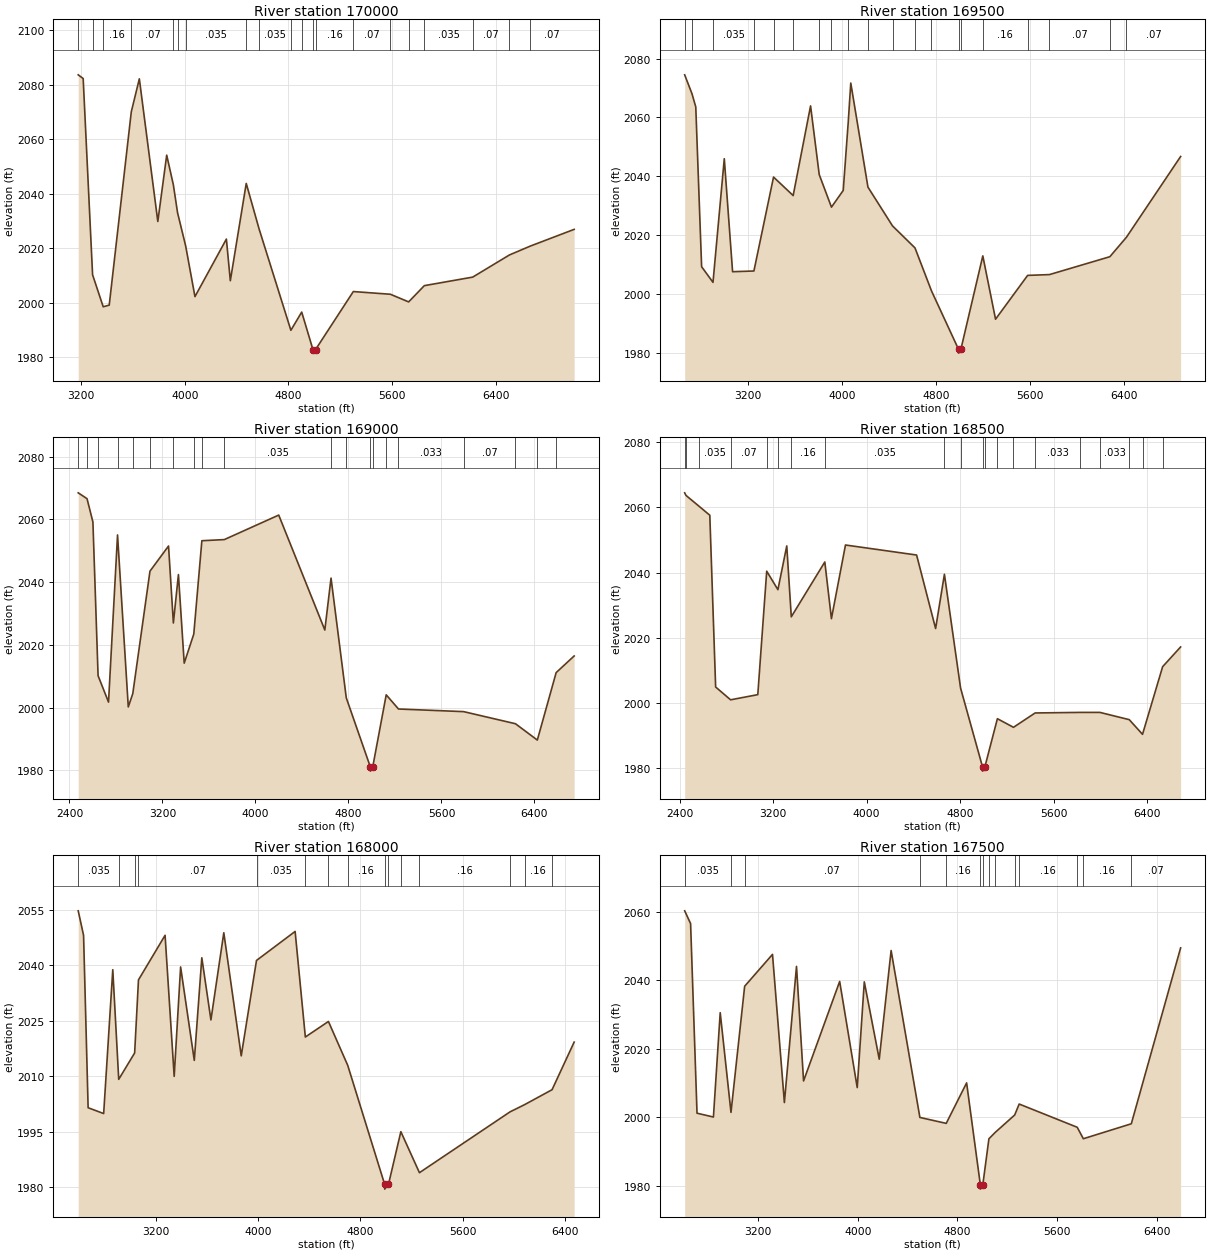
Type RM Length L Ch R = 1,170000,500,500,500
BEGIN DESCRIPTION:
Sweetwater Creek 339.0
END DESCRIPTION:
XS GIS Cut Line= 4
      1397207.91      6870110.45      1398860.46      6869340.04
      1399212.17      6869003.32      1400309.65      6867952.71
#Sta/Elev= 30
  3176.7 2083.71  3215.0 2082.35  3287.7 2010.25  3369.7 1998.49  3416.2 1999.10
  3586.6 2070.12  3648.7 2082.24  3791.4 2029.83  3860.0 2054.20  3911.4 2043.30
  3943.9 2033.03  4006.2 2020.89  4078.2 2002.22  4320.9 2023.36  4351.3 2008.06
  4474.2 2043.81  4573.3 2027.10  4818.9 1989.85  4902.5 1996.54  4989.2 1982.76
  4989.5 1981.46  5009.3 1982.76  5301.0 2004.08  5587.3 2003.09  5728.2 2000.28
  5849.3 2006.25  6223.0 2009.39  6506.1 2017.52  6667.9 2020.79  7006.2 2026.93
#Mann=20,-1,0
  3176.7   0.035       0  3287.7    0.07       0  3369.7    0.16       0
  3586.6    0.07       0  3911.4    0.16       0  3943.9    0.07       0
  4006.2   0.035       0  4474.2    0.07       0  4573.3   0.035       0
  4818.9    0.07       0  4902.5    0.16       0  4989.2    0.07       0
  5009.3    0.16       0  5301.0    0.07       0  5587.3   0.035       0
  5728.2    0.07       0  5849.3   0.035       0  6223.0    0.07       0
  6506.1   0.035       0  6667.9    0.07       0
Bank Sta=4989.2,5009.3
Exp/Cntr=0.3,0.1

Type RM Length L Ch R = 1,169500,500,500,500
BEGIN DESCRIPTION:
Sweetwater Creek 338.0
END DESCRIPTION:
XS GIS Cut Line= 4
      1397880.61      6871195.55      1399320.62      6869354.02
      1399458.41      6869222.81      1400680.31      6868059.32
#Sta/Elev= 30
  2662.3 2074.51  2724.2 2068.11  2756.6 2063.60  2806.3 2009.25  2903.0 2003.93
  2998.9 2045.98  3069.5 2007.55  3250.7 2007.79  3417.6 2039.74  3584.4 2033.45
  3732.3 2063.94  3805.9 2040.58  3909.8 2029.51  4009.9 2035.19  4052.6 2058.50
  4074.1 2071.71  4220.0 2036.32  4428.8 2023.13  4619.8 2015.65  4760.1 2001.03
  4989.9 1981.16  4990.2 1979.86  5009.9 1981.16  5196.3 2012.93  5304.5 1991.40
  5577.4 2006.30  5762.8 2006.57  6276.0 2012.65  6416.5 2019.24  6877.5 2046.73
#Mann=20,-1,0
  2662.3    0.07       0  2724.2   0.035       0  2903.0   0.035       0
  3250.7   0.063       0  3417.6    0.07       0  3584.4    0.16       0
  3805.9    0.07       0  3909.8   0.035       0  4052.6    0.07       0
  4220.0    0.16       0  4428.8    0.07       0  4619.8   0.035       0
  4760.1    0.16       0  4989.9    0.07       0  5009.9    0.16       0
  5196.3    0.16       0  5577.4   0.035       0  5762.8    0.07       0
  6276.0   0.035       0  6416.5    0.07       0
Bank Sta=4989.9,5009.9
Exp/Cntr=0.3,0.1

Type RM Length L Ch R = 1,169000,500,500,500
BEGIN DESCRIPTION:
Sweetwater Creek 337.0
END DESCRIPTION:
XS GIS Cut Line= 4
      1398010.86      6871412.52      1399743.41      6869575.98
      1399855.00      6869538.00      1401391.86      6869014.95
#Sta/Elev= 30
  2475.2 2068.50  2551.1 2066.63  2601.7 2059.18  2646.1 2010.16  2736.0 2001.73
  2813.5 2055.06  2905.9 2000.19  2944.7 2004.44  3092.5 2043.51  3252.2 2051.53
  3293.8 2026.98  3337.2 2042.42  3387.0 2014.16  3469.4 2023.44  3538.9 2053.22
  3731.9 2053.58  4200.1 2061.40  4596.6 2024.73  4650.0 2041.29  4781.2 2003.08
  4988.5 1981.01  4988.8 1979.71  5008.5 1981.01  5124.7 2004.05  5230.3 1999.53
  5790.7 1998.69  6236.6 1994.83  6424.5 1989.62  6586.5 2011.14  6741.3 2016.45
#Mann=20,-1,0
  2475.2    0.16       0  2551.1   0.035       0  2646.1    0.07       0
  2813.5    0.07       0  2944.7   0.094       0  3092.5    0.07       0
  3293.8    0.16       0  3469.4    0.07       0  3538.9   0.035       0
  3731.9   0.035       0  4650.0   0.035       0  4781.2    0.16       0
  4988.5    0.07       0  5008.5    0.16       0  5124.7    0.16       0
  5230.3   0.033       0  5790.7    0.07       0  6236.6    0.07       0
  6424.5    0.16       0  6586.5    0.07       0
Bank Sta=4988.5,5008.5
Exp/Cntr=0.3,0.1

Type RM Length L Ch R = 1,168500,500,500,500
BEGIN DESCRIPTION:
Sweetwater Creek 336.0
END DESCRIPTION:
XS GIS Cut Line= 3
      1398108.45      6871705.55      1399989.70      6869973.45
      1401430.15      6869096.87
#Sta/Elev= 30
  2442.8 2064.50  2453.6 2063.72  2567.5 2060.32  2657.8 2057.61  2707.7 2004.81
  2835.7 2000.87  3068.4 2002.46  3144.7 2040.41  3240.5 2034.73  3316.2 2048.18
  3355.0 2026.39  3641.8 2043.24  3698.5 2025.82  3818.7 2048.46  4427.2 2045.38
  4589.9 2022.78  4665.2 2039.46  4803.4 2004.49  4991.3 1980.25  4991.6 1978.95
  5011.3 1980.25  5118.5 1995.07  5256.2 1992.42  5441.5 1996.83  5826.2 1997.00
  5995.7 1997.00  6246.7 1994.77  6360.2 1990.26  6532.3 2011.05  6686.2 2017.12
#Mann=20,-1,0
  2442.8    0.07       0  2453.6    0.16       0  2567.5   0.035       0
  2835.7    0.07       0  3144.7    0.16       0  3240.5    0.07       0
  3355.0    0.16       0  3641.8   0.035       0  4665.2   0.035       0
  4803.4    0.16       0  4991.3    0.07       0  5011.3    0.16       0
  5118.5    0.07       0  5256.2    0.16       0  5441.5   0.033       0
  5826.2    0.07       0  5995.7   0.033       0  6246.7    0.07       0
  6360.2    0.16       0  6532.3    0.07       0
Bank Sta=4991.3,5011.3
Exp/Cntr=0.3,0.1

Type RM Length L Ch R = 1,168000,500,500,500
BEGIN DESCRIPTION:
Sweetwater Creek 335.0
END DESCRIPTION:
XS GIS Cut Line= 3
      1398358.04      6871748.93      1400311.80      6870344.77
      1401567.97      6869579.14
#Sta/Elev= 30
  2594.0 2054.67  2635.9 2048.05  2671.5 2001.49  2793.0 1999.92  2864.3 2038.77
  2910.7 2009.16  3035.2 2016.28  3065.2 2036.02  3273.1 2048.06  3344.3 2009.97
  3394.6 2039.51  3501.5 2014.28  3560.3 2041.99  3631.5 2025.21  3732.2 2048.75
  3868.5 2015.50  3987.8 2041.27  4289.7 2049.10  4369.7 2020.59  4550.2 2024.79
  4701.0 2012.94  4989.6 1980.81  4990.1 1979.51  5019.7 1980.81  5116.3 1995.02
  5261.6 1983.95  5969.6 2000.37  6084.0 2002.33  6298.5 2006.36  6471.1 2019.22
#Mann=15,-1,0
  2594.0   0.035       0  2910.7   0.063       0  3035.2   0.094       0
  3065.2    0.07       0  3987.8   0.035       0  4369.7    0.07       0
  4550.2   0.035       0  4701.0    0.16       0  4989.6    0.07       0
  5019.7    0.16       0  5116.3    0.07       0  5261.6    0.16       0
  5969.6    0.07       0  6084.0    0.16       0  6298.5    0.07       0
Bank Sta=4989.6,5019.7
Exp/Cntr=0.3,0.1

Type RM Length L Ch R = 1,167500,500,500,500
BEGIN DESCRIPTION:
Sweetwater Creek 334.0
END DESCRIPTION:
XS GIS Cut Line= 3
      1398423.11      6871890.00      1400530.60      6870763.43
      1401704.99      6869688.01
#Sta/Elev= 30
  2610.3 2060.23  2657.8 2056.51  2709.4 2001.17  2841.1 2000.05  2895.6 2030.51
  2982.2 2001.41  3091.9 2038.22  3315.5 2047.52  3410.9 2004.27  3508.2 2044.01
  3564.9 2010.58  3854.8 2039.62  3995.8 2008.65  4052.5 2039.50  4172.6 2016.93
  4267.9 2048.65  4498.9 1999.93  4710.4 1998.20  4874.1 2010.01  4984.2 1980.31
  4984.5 1979.01  5004.2 1980.31  5053.2 1993.70  5103.0 1995.54  5260.0 2000.64
  5296.3 2003.84  5762.2 1997.06  5811.4 1993.72  6196.5 1998.08  6592.4 2049.41
#Mann=14,-1,0
  2610.3   0.035       0  2982.2   0.063       0  3091.9    0.07       0
  4498.9   0.035       0  4710.4    0.16       0  4984.2    0.07       0
  5004.2    0.16       0  5053.2    0.07       0  5103.0    0.16       0
  5260.0    0.07       0  5296.3    0.16       0  5762.2    0.07       0
  5811.4    0.16       0  6196.5    0.07       0
Bank Sta=4984.2,5004.2
Exp/Cntr=0.3,0.1

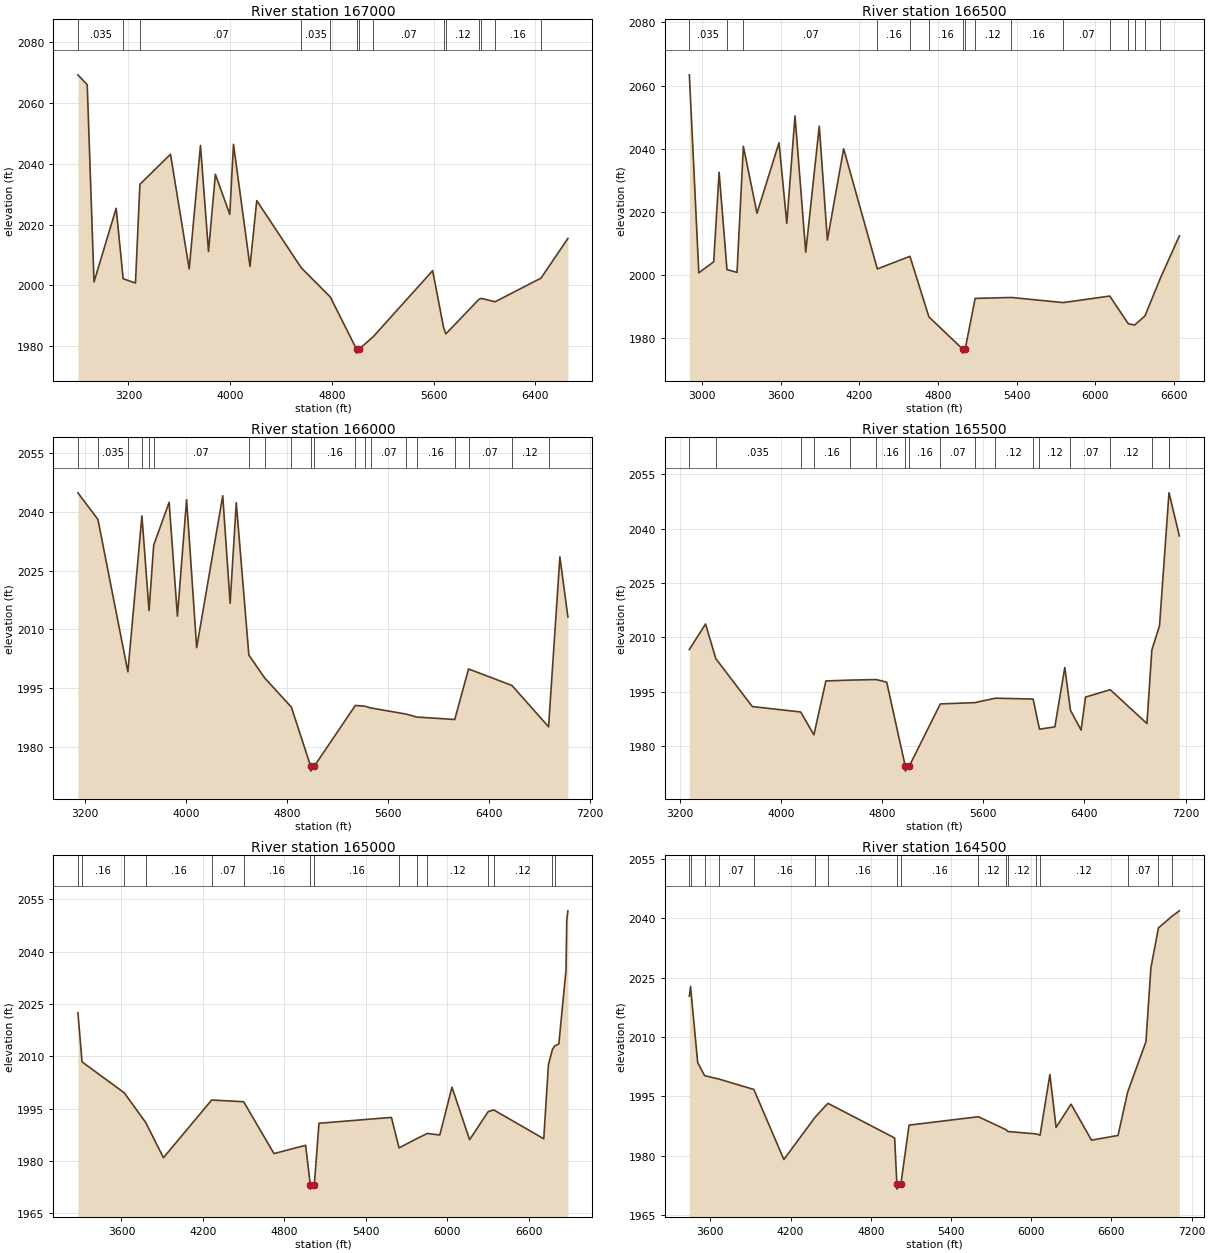
Type RM Length L Ch R = 1,167000,500,500,500
BEGIN DESCRIPTION:
Sweetwater Creek 333.0
END DESCRIPTION:
XS GIS Cut Line= 3
      1398477.39      6872063.60      1400504.76      6871215.80
      1401717.57      6870087.20
#Sta/Elev= 30
  2802.5 2069.26  2875.8 2065.99  2929.1 2001.10  3103.4 2025.34  3158.4 2002.17
  3255.2 2000.76  3290.2 2033.24  3530.7 2043.12  3677.9 2005.39  3766.6 2046.02
  3829.6 2011.12  3883.8 2036.53  3997.0 2023.36  4026.2 2046.40  4156.1 2006.22
  4209.1 2027.88  4559.7 2005.74  4787.6 1996.18  4994.0 1978.99  4994.3 1977.69
  5014.0 1978.99  5125.9 1983.11  5592.9 2004.83  5679.1 1986.05  5696.9 1984.02
  5958.2 1995.44  5974.8 1995.70  6084.0 1994.59  6445.2 2002.37  6656.7 2015.43
#Mann=14,-1,0
  2802.5   0.035       0  3158.4   0.063       0  3290.2    0.07       0
  4559.7   0.035       0  4787.6    0.16       0  4994.0    0.07       0
  5014.0    0.16       0  5125.9    0.07       0  5679.1    0.16       0
  5696.9    0.12       0  5958.2    0.16       0  5974.8    0.12       0
  6084.0    0.16       0  6445.2    0.07       0
Bank Sta=4994,5014
Exp/Cntr=0.3,0.1

Type RM Length L Ch R = 1,166500,500,500,500
BEGIN DESCRIPTION:
Sweetwater Creek 332.0
END DESCRIPTION:
XS GIS Cut Line= 3
      1398575.03      6872182.95      1400605.41      6871660.17
      1401789.40      6870522.63
#Sta/Elev= 30
  2903.4 2063.43  2975.6 2000.78  3089.2 2004.27  3130.5 2032.61  3190.5 2001.80
  3267.1 2000.92  3315.6 2040.82  3419.5 2019.64  3587.5 2041.94  3646.9 2016.47
  3709.6 2050.43  3791.4 2007.32  3894.7 2047.21  3956.6 2011.15  4080.6 2040.04
  4337.8 2002.02  4586.5 2006.01  4731.2 1986.84  4988.3 1976.67  4988.6 1975.37
  5008.3 1976.67  5084.1 1992.69  5361.3 1992.98  5755.6 1991.36  6111.2 1993.43
  6252.3 1984.67  6301.2 1984.27  6379.1 1987.12  6497.3 1999.08  6641.9 2012.46
#Mann=16,-1,0
  2903.4   0.035       0  3190.5   0.063       0  3315.6    0.07       0
  4337.8    0.16       0  4586.5   0.035       0  4731.2    0.16       0
  4988.3    0.07       0  5008.3    0.16       0  5084.1    0.12       0
  5361.3    0.16       0  5755.6    0.07       0  6111.2    0.16       0
  6252.3    0.12       0  6301.2    0.16       0  6379.1    0.12       0
  6497.3    0.07       0
Bank Sta=4988.3,5008.3
Exp/Cntr=0.3,0.1

Type RM Length L Ch R = 1,166000,500,500,500
BEGIN DESCRIPTION:
Sweetwater Creek 331.0
END DESCRIPTION:
XS GIS Cut Line= 4
      1398857.14      6873051.03      1400455.41      6872102.17
      1400991.74      6871698.80      1401856.76      6870659.60
#Sta/Elev= 30
  3141.3 2044.88  3299.9 2038.08  3537.2 1999.20  3648.4 2039.00  3704.7 2014.83
  3741.7 2031.53  3863.9 2042.46  3929.6 2013.41  4002.3 2043.14  4082.2 2005.36
  4288.7 2044.14  4347.2 2016.71  4395.9 2042.35  4495.6 2003.48  4620.7 1997.63
  4832.4 1990.17  4984.7 1975.14  4985.2 1973.84  5014.8 1975.14  5339.1 1990.60
  5412.4 1990.43  5460.7 1989.97  5740.1 1988.41  5824.5 1987.65  6126.9 1987.02
  6236.1 1999.92  6580.0 1995.71  6869.9 1985.15  6959.7 2028.53  7023.2 2013.18
#Mann=20,-1,0
  3141.3    0.07       0  3299.9   0.035       0  3537.2   0.063       0
  3648.4    0.07       0  3704.7   0.035       0  3741.7    0.07       0
  4495.6    0.16       0  4620.7   0.035       0  4832.4    0.16       0
  4984.7    0.07       0  5014.8    0.16       0  5339.1    0.07       0
  5412.4    0.16       0  5460.7    0.07       0  5740.1    0.12       0
  5824.5    0.16       0  6126.9    0.12       0  6236.1    0.07       0
  6580.0    0.12       0  6869.9    0.07       0
Bank Sta=4984.7,5014.8
Exp/Cntr=0.3,0.1

Type RM Length L Ch R = 1,165500,500,500,500
BEGIN DESCRIPTION:
Sweetwater Creek 330.0
END DESCRIPTION:
XS GIS Cut Line= 3
      1400326.05      6874073.35      1400688.84      6872388.88
      1402004.98      6870688.03
#Sta/Elev= 30
  3276.9 2006.66  3405.1 2013.70  3486.1 2004.14  3774.6 1990.91  4156.6 1989.42
  4261.6 1983.12  4356.4 1997.98  4543.9 1998.21  4755.3 1998.36  4837.2 1997.64
  4984.3 1974.39  4984.8 1973.09  5014.4 1974.39  5260.8 1991.64  5532.6 1991.99
  5697.2 1993.22  5994.6 1992.98  6045.0 1984.67  6166.4 1985.30  6245.2 2001.70
  6289.9 1989.87  6373.7 1984.43  6409.1 1993.53  6604.4 1995.56  6894.4 1986.23
  6933.3 2006.54  6994.0 2013.25  7068.7 2049.89  7069.3 2049.90  7150.6 2038.01
#Mann=18,-1,0
  3276.9    0.07       0  3486.1   0.035       0  4156.6    0.07       0
  4261.6    0.16       0  4543.9    0.07       0  4755.3    0.16       0
  4984.3    0.07       0  5014.4    0.16       0  5260.8    0.07       0
  5532.6    0.16       0  5697.2    0.12       0  5994.6    0.16       0
  6045.0    0.12       0  6289.9    0.07       0  6604.4    0.12       0
  6933.3    0.07       0  7068.7    0.12       0  7069.3    0.07       0
Bank Sta=4984.3,5014.4
Exp/Cntr=0.3,0.1

Type RM Length L Ch R = 1,165000,500,500,500
BEGIN DESCRIPTION:
Sweetwater Creek 329.0
END DESCRIPTION:
XS GIS Cut Line= 3
      1400520.14      6874097.68      1401128.93      6872487.84
      1401954.98      6870788.03
#Sta/Elev= 30
  3278.9 2022.47  3309.4 2008.38  3620.2 1999.52  3778.6 1990.99  3909.3 1980.90
  4264.5 1997.44  4500.4 1996.96  4723.8 1982.09  4957.1 1984.46  4991.3 1973.20
  4991.7 1971.90  5021.3 1973.20  5055.4 1990.78  5589.1 1992.46  5645.5 1983.72
  5774.6 1986.34  5854.3 1987.86  5945.5 1987.41  6035.7 2001.11  6165.5 1986.07
  6302.5 1994.12  6343.6 1994.60  6712.0 1986.34  6746.1 2007.52  6776.1 2011.97
  6791.8 2012.91  6823.2 2013.54  6875.9 2034.73  6881.4 2048.96  6889.9 2051.68
#Mann=15,-1,0
  3278.9   0.035       0  3309.4    0.16       0  3620.2    0.07       0
  3778.6    0.16       0  4264.5    0.07       0  4500.4    0.16       0
  4991.3    0.07       0  5021.3    0.16       0  5645.5    0.12       0
  5774.6    0.16       0  5854.3    0.12       0  6302.5    0.07       0
  6343.6    0.12       0  6776.1    0.07       0  6791.8    0.12       0
Bank Sta=4991.3,5021.3
Exp/Cntr=0.3,0.1

Type RM Length L Ch R = 1,164500,500,500,500
BEGIN DESCRIPTION:
Sweetwater Creek 328.0
END DESCRIPTION:
XS GIS Cut Line= 3
      1400615.36      6874172.18      1401385.97      6872819.14
      1402105.00      6870837.99
#Sta/Elev= 30
  3442.9 2020.29  3451.8 2022.75  3505.3 2003.54  3557.0 2000.24  3661.2 1999.41
  3925.3 1996.76  4149.7 1979.08  4384.4 1989.80  4479.4 1993.26  4978.3 1984.52
  4994.9 1972.91  4995.4 1971.61  5025.0 1972.91  5086.3 1987.76  5604.7 1989.88
  5809.2 1986.64  5826.2 1986.14  6036.7 1985.55  6066.1 1985.23  6139.5 2000.52
  6185.8 1987.19  6297.6 1993.05  6450.7 1983.97  6649.0 1985.15  6721.0 1996.09
  6858.0 2008.84  6894.8 2027.42  6951.2 2037.52  7053.5 2040.48  7107.6 2041.83
#Mann=17,-1,0
  3442.9   0.035       0  3451.8    0.07       0  3557.0    0.16       0
  3661.2    0.07       0  3925.3    0.16       0  4384.4    0.07       0
  4479.4    0.16       0  4994.9    0.07       0  5025.0    0.16       0
  5604.7    0.12       0  5809.2    0.16       0  5826.2    0.12       0
  6036.7    0.16       0  6066.1    0.12       0  6721.0    0.07       0
  6951.2    0.16       0  7053.5    0.07       0
Bank Sta=4994.9,5025
Exp/Cntr=0.3,0.1

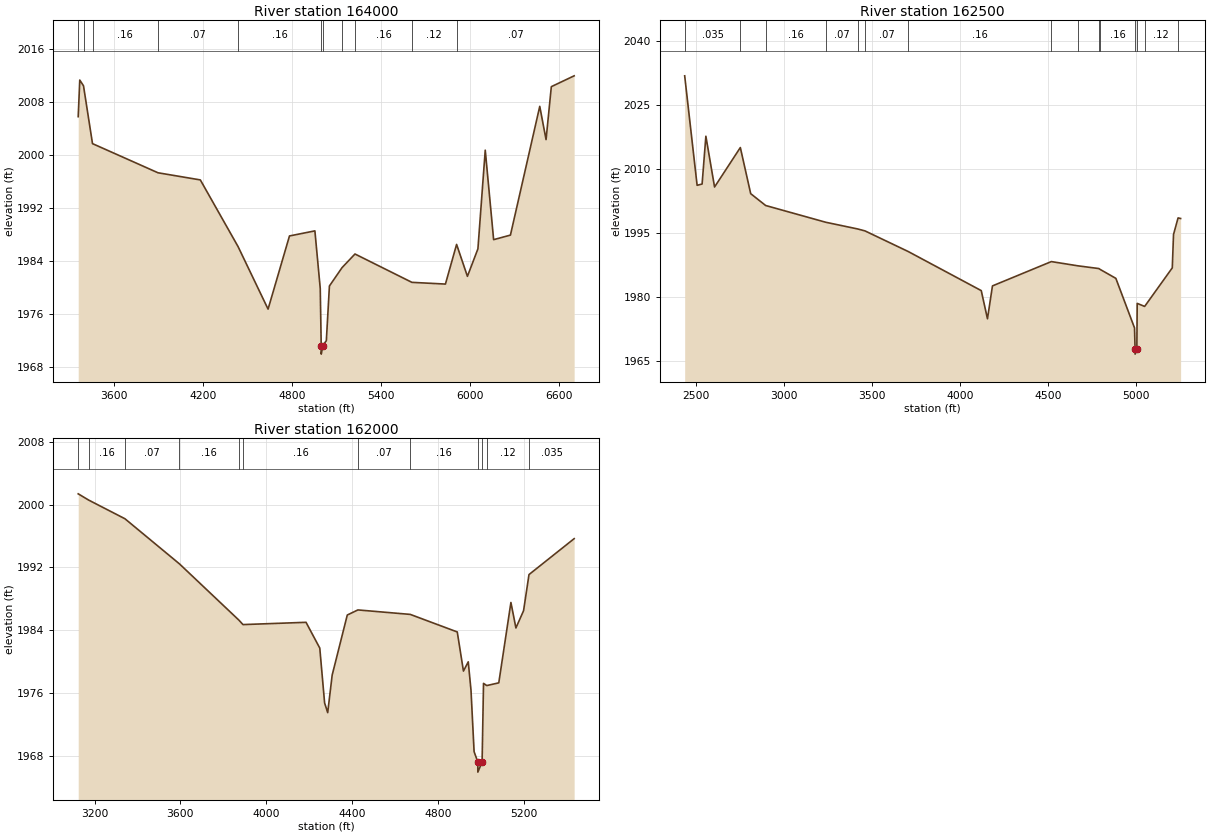
Type RM Length L Ch R = 1,164000,1500,1500,1500
BEGIN DESCRIPTION:
Sweetwater Creek 326.0
END DESCRIPTION:
XS GIS Cut Line= 5
      1400722.52      6874260.36      1401507.22      6873491.65
      1401807.36      6873038.52      1401965.01      6872486.25
      1402784.82      6871710.06
#Sta/Elev= 30
  3358.0 2005.83  3368.5 2011.37  3393.7 2010.50  3454.4 2001.75  3896.2 1997.34
  4181.7 1996.26  4436.3 1986.17  4638.7 1976.71  4783.1 1987.78  4954.5 1988.55
  4990.6 1979.84  4997.1 1971.20  4997.3 1969.90  5007.1 1971.20  5031.7 1971.93
  5052.5 1980.21  5137.8 1982.99  5224.9 1985.05  5609.0 1980.76  5835.0 1980.50
  5910.4 1986.50  5983.4 1981.67  6054.2 1985.83  6103.6 2000.76  6160.2 1987.22
  6273.5 1987.91  6471.3 2007.39  6513.8 2002.36  6549.4 2010.37  6703.3 2012.01
#Mann=11,-1,0
  3358.0   0.035       0  3393.7    0.07       0  3454.4    0.16       0
  3896.2    0.07       0  4436.3    0.16       0  4997.1    0.07       0
  5007.1    0.16       0  5137.8    0.12       0  5224.9    0.16       0
  5609.0    0.12       0  5910.4    0.07       0
Bank Sta=4997.1,5007.1
Exp/Cntr=0.3,0.1

Type RM Length L Ch R = 1,162500,500,500,500
BEGIN DESCRIPTION:
Sweetwater Creek 324.0
END DESCRIPTION:
XS GIS Cut Line= 3
      1400555.03      6874537.98      1402405.33      6872763.46
      1402655.04      6872738.00
#Sta/Elev= 30
  2436.3 2031.76  2506.9 2006.14  2535.2 2006.45  2556.6 2017.63  2605.9 2005.75
  2752.2 2014.98  2811.0 2004.19  2895.9 2001.42  3237.2 1997.50  3417.4 1995.94
  3459.6 1995.48  3704.7 1990.66  4119.5 1981.51  4154.8 1974.92  4183.1 1982.61
  4517.3 1988.30  4667.8 1987.31  4786.8 1986.67  4795.8 1986.43  4883.4 1984.38
  4989.4 1972.78  4992.5 1967.95  4992.7 1966.65  5002.6 1967.95  5004.6 1978.52
  5046.9 1977.81  5203.7 1986.83  5210.8 1994.65  5236.6 1998.52  5251.0 1998.38
#Mann=15,-1,0
  2436.3   0.035       0  2752.2    0.07       0  2895.9    0.16       0
  3237.2    0.07       0  3417.4    0.16       0  3459.6    0.07       0
  3704.7    0.16       0  4517.3    0.07       0  4667.8    0.16       0
  4786.8    0.07       0  4795.8    0.16       0  4992.5    0.07       0
  5002.6    0.16       0  5046.9    0.12       0  5236.6   0.035       0
Bank Sta=4992.5,5002.6
Exp/Cntr=0.3,0.1

Type RM Length L Ch R = 1,162000,500,500,500
BEGIN DESCRIPTION:
Sweetwater Creek 323.0
END DESCRIPTION:
XS GIS Cut Line= 3
      1401136.79      6874362.27      1402601.27      6873189.97
      1402855.01      6872837.99
#Sta/Elev= 30
  3124.1 2001.39  3172.9 2000.59  3341.8 1998.21  3595.4 1992.46  3872.8 1985.27
  3891.5 1984.71  4185.2 1985.00  4249.2 1981.71  4271.7 1974.71  4286.1 1973.48
  4306.9 1978.27  4377.3 1985.93  4426.8 1986.58  4670.5 1986.01  4889.5 1983.77
  4918.3 1978.78  4940.7 1979.96  4953.5 1976.33  4967.9 1968.50  4985.1 1967.19
  4985.4 1965.89  5005.2 1967.19  5011.8 1977.21  5026.9 1976.93  5082.9 1977.28
  5139.4 1987.53  5162.7 1984.28  5198.3 1986.48  5223.6 1991.09  5433.9 1995.67
#Mann=12,-1,0
  3124.1    0.07       0  3172.9    0.16       0  3341.8    0.07       0
  3595.4    0.16       0  3872.8    0.07       0  3891.5    0.16       0
  4426.8    0.07       0  4670.5    0.16       0  4985.1    0.07       0
  5005.2    0.16       0  5026.9    0.12       0  5223.6   0.035       0
Bank Sta=4985.1,5005.2
Exp/Cntr=0.3,0.1