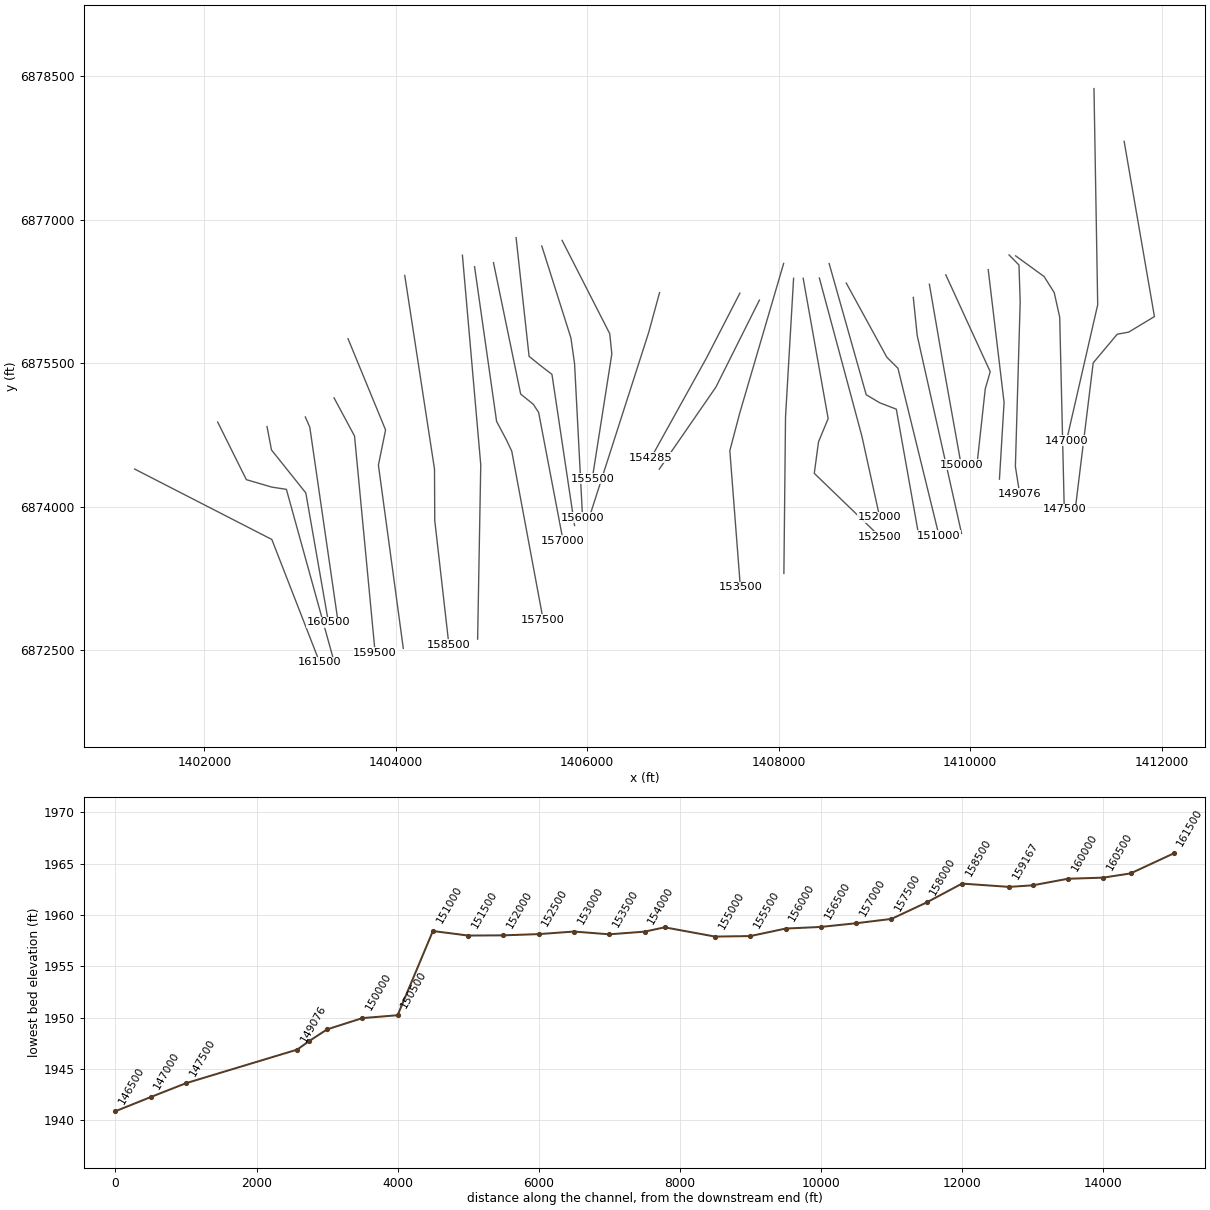
HEC-RAS study Sweetwater Creek.prj: Sweetwater Creek Base Level Engineering

--- Sweetwater Creek.g01 (geometry) --- (continued)

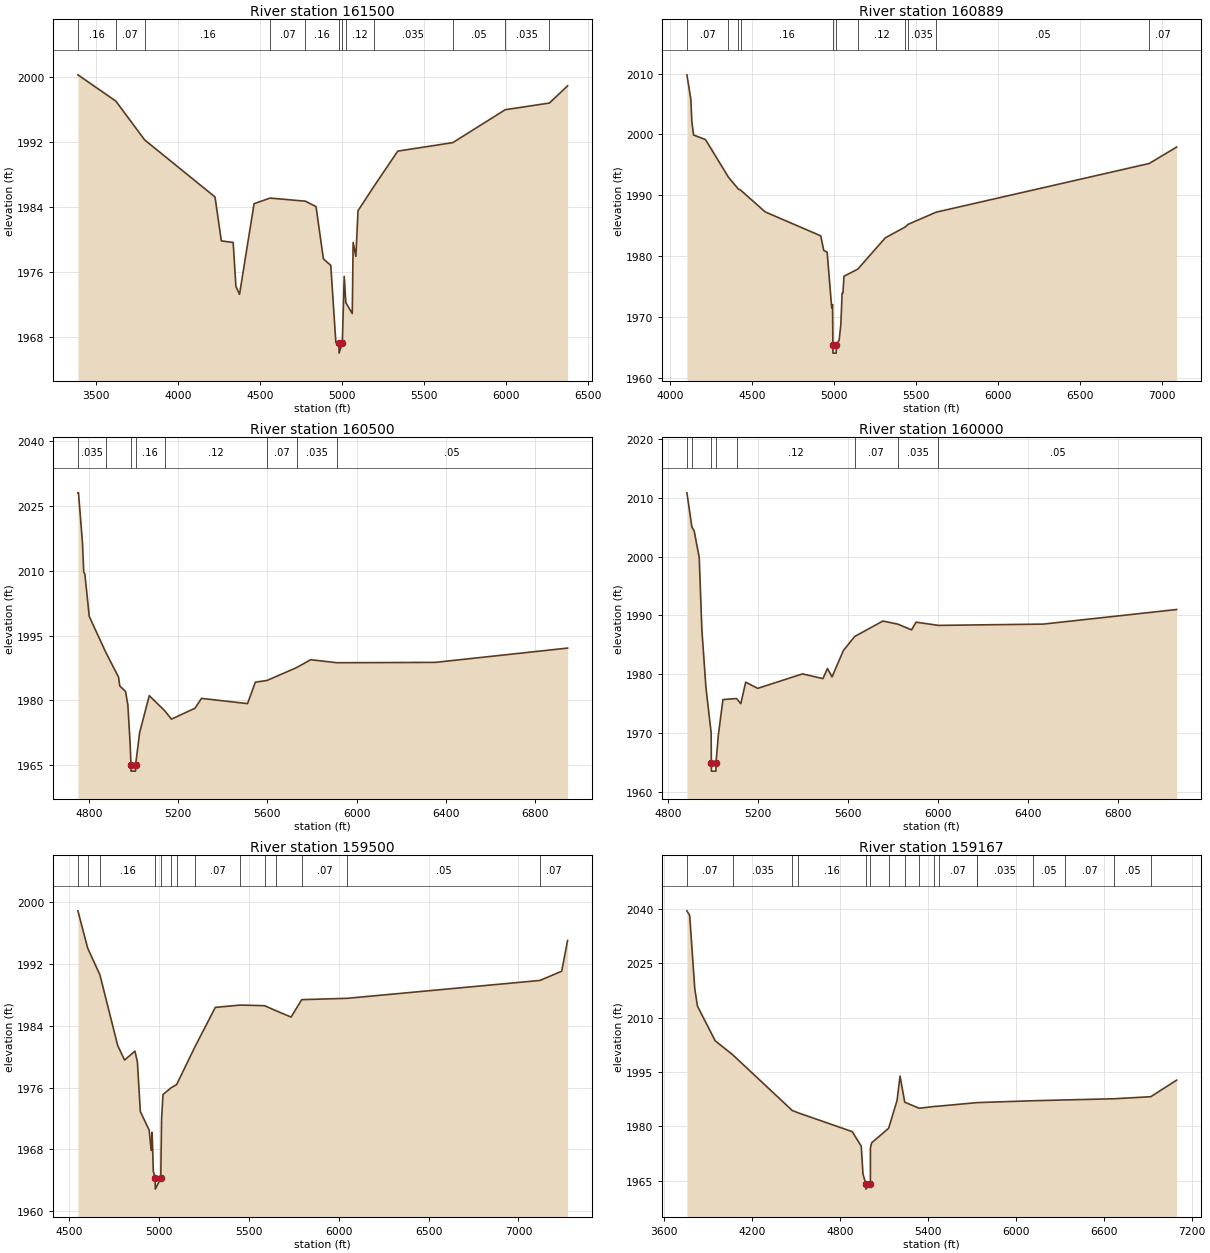
Type RM Length L Ch R = 1,161500,611,611,611
BEGIN DESCRIPTION:
Sweetwater Creek 322.0
END DESCRIPTION:
XS GIS Cut Line= 3
      1401272.54      6874393.54      1402705.33      6873657.48
      1403204.43      6872373.90
#Sta/Elev= 30
  3389.2 2000.31  3620.7 1997.07  3796.7 1992.28  4225.8 1985.25  4264.5 1979.83
  4336.7 1979.64  4353.2 1974.23  4375.4 1973.24  4464.2 1984.42  4562.2 1985.11
  4776.7 1984.73  4842.2 1984.06  4887.2 1977.61  4932.2 1976.81  4963.2 1967.29
  4982.6 1967.29  4982.9 1965.99  5002.7 1967.29  5014.2 1975.46  5024.1 1972.22
  5063.3 1970.87  5068.6 1979.64  5085.3 1977.92  5098.5 1983.56  5196.1 1986.57
  5340.7 1990.90  5676.9 1991.95  5996.9 1996.01  6266.1 1996.83  6377.2 1998.96
#Mann=12,-1,0
  3389.2    0.16       0  3620.7    0.07       0  3796.7    0.16       0
  4562.2    0.07       0  4776.7    0.16       0  4982.6    0.07       0
  5002.7    0.16       0  5024.1    0.12       0  5196.1   0.035       0
  5676.9    0.05       0  5996.9   0.035       0  6266.1    0.07       0
Bank Sta=4982.6,5002.7
Exp/Cntr=0.3,0.1

Type RM Length L Ch R = 1,160889,389,389,389
BEGIN DESCRIPTION:
Sweetwater Creek 321.0
END DESCRIPTION:
XS GIS Cut Line= 5
      1402139.71      6874885.06      1402438.95      6874282.83
      1402705.20      6874204.87      1402857.37      6874181.43
      1403359.73      6872364.89
#Sta/Elev= 30
  4102.8 2009.81  4126.7 2005.80  4133.0 2002.10  4143.5 1999.91  4216.3 1999.16
  4356.1 1992.98  4416.7 1991.02  4431.5 1990.83  4580.3 1987.27  4919.6 1983.33
  4937.9 1980.93  4958.7 1980.64  4986.5 1971.47  4991.7 1972.02  4993.7 1965.44
  4994.0 1964.04  5014.0 1964.04  5014.3 1965.44  5031.7 1966.14  5042.1 1968.72
  5050.0 1973.91  5055.1 1973.91  5061.3 1976.68  5145.7 1977.86  5314.0 1983.01
  5434.9 1984.78  5452.8 1985.22  5623.7 1987.22  6924.4 1995.23  7091.4 1997.93
#Mann=11,-1,0
  4102.8    0.07       0  4356.1    0.16       0  4416.7    0.07       0
  4431.5    0.16       0  4993.7    0.07       0  5014.3    0.16       0
  5145.7    0.12       0  5434.9    0.07       0  5452.8   0.035       0
  5623.7    0.05       0  6924.4    0.07       0
Bank Sta=4993.7,5014.3
Exp/Cntr=0.3,0.1

Type RM Length L Ch R = 1,160500,500,500,500
BEGIN DESCRIPTION:
Sweetwater Creek 320.0
END DESCRIPTION:
XS GIS Cut Line= 4
      1402654.99      6874838.04      1402701.72      6874593.36
      1403060.25      6874144.08      1403296.38      6872793.37
#Sta/Elev= 30
  4750.9 2028.05  4753.5 2028.05  4771.3 2016.61  4777.0 2009.73  4782.1 2009.25
  4801.8 1999.44  4875.2 1991.21  4933.3 1985.36  4938.4 1983.36  4964.7 1982.05
  4974.9 1978.91  4985.1 1969.91  4988.8 1965.03  4989.1 1963.63  5009.1 1963.63
  5009.4 1965.03  5027.7 1972.57  5070.8 1981.10  5139.5 1977.64  5170.2 1975.66
  5275.9 1978.19  5304.7 1980.47  5511.2 1979.26  5546.5 1984.23  5598.3 1984.61
  5732.2 1987.62  5794.2 1989.42  5911.9 1988.72  6352.5 1988.80  6946.0 1992.11
#Mann=8,-1,0
  4750.9   0.035       0  4875.2    0.16       0  4988.8    0.07       0
  5009.4    0.16       0  5139.5    0.12       0  5598.3    0.07       0
  5732.2   0.035       0  5911.9    0.05       0
Bank Sta=4988.8,5009.4
Exp/Cntr=0.3,0.1

Type RM Length L Ch R = 1,160000,500,500,500
BEGIN DESCRIPTION:
Sweetwater Creek 319.0
END DESCRIPTION:
XS GIS Cut Line= 3
      1403054.98      6874938.05      1403101.77      6874831.68
      1403397.63      6872791.32
#Sta/Elev= 30
  4883.8 2010.86  4906.0 2005.04  4916.1 2004.39  4938.5 1999.87  4950.4 1987.54
  4968.3 1977.79  4991.6 1970.04  4992.5 1964.92  4992.8 1963.52  5012.8 1963.52
  5013.1 1964.92  5023.9 1969.76  5044.1 1975.69  5104.7 1975.87  5123.5 1974.99
  5145.2 1978.65  5198.7 1977.60  5397.8 1980.06  5488.7 1979.26  5509.0 1980.97
  5529.2 1979.55  5579.7 1984.03  5629.8 1986.42  5755.3 1989.05  5822.1 1988.52
  5882.8 1987.55  5903.0 1988.86  6002.3 1988.31  6468.9 1988.53  7061.7 1991.01
#Mann=8,-1,0
  4883.8   0.035       0  4906.0    0.16       0  4992.5    0.07       0
  5013.1    0.16       0  5104.7    0.12       0  5629.8    0.07       0
  5822.1   0.035       0  6002.3    0.05       0
Bank Sta=4992.5,5013.1
Exp/Cntr=0.3,0.1

Type RM Length L Ch R = 1,159500,333,333,333
BEGIN DESCRIPTION:
Sweetwater Creek 318.0
END DESCRIPTION:
XS GIS Cut Line= 3
      1403355.02      6875137.96      1403569.05      6874738.82
      1403784.22      6872475.23
#Sta/Elev= 30
  4547.1 1998.82  4601.6 1994.00  4669.6 1990.56  4768.8 1981.42  4807.0 1979.55
  4864.8 1980.70  4878.4 1979.31  4894.7 1972.90  4944.2 1970.49  4954.8 1967.88
  4960.5 1970.21  4966.9 1965.20  4977.6 1964.28  4978.0 1962.88  5008.5 1964.28
  5013.0 1971.93  5020.9 1975.10  5066.7 1975.98  5096.6 1976.37  5198.7 1981.25
  5312.2 1986.35  5451.9 1986.65  5586.8 1986.57  5648.0 1985.94  5734.1 1985.10
  5793.3 1987.35  6046.3 1987.52  7119.7 1989.83  7240.9 1991.02  7273.8 1995.00
#Mann=14,-1,0
  4547.1    0.07       0  4601.6   0.035       0  4669.6    0.16       0
  4977.6    0.07       0  5008.5    0.16       0  5066.7    0.16       0
  5096.6    0.12       0  5198.7    0.07       0  5451.9   0.035       0
  5586.8    0.07       0  5648.0   0.035       0  5793.3    0.07       0
  6046.3    0.05       0  7119.7    0.07       0
Bank Sta=4977.6,5008.5
Exp/Cntr=0.3,0.1

Type RM Length L Ch R = 1,159167,667,667,667
BEGIN DESCRIPTION:
Sweetwater Creek 317.0
END DESCRIPTION:
XS GIS Cut Line= 4
      1403501.07      6875756.31      1403893.24      6874802.71
      1403818.49      6874435.22      1404078.43      6872518.58
#Sta/Elev= 30
  3756.8 2039.45  3775.7 2038.18  3810.5 2017.92  3829.1 2013.15  3949.6 2003.63
  4068.9 1999.78  4475.1 1984.42  4513.5 1983.80  4884.5 1978.58  4945.8 1974.58
  4957.9 1966.88  4977.5 1964.13  4977.9 1962.73  5008.4 1964.13  5008.5 1974.07
  5017.2 1975.51  5132.9 1979.51  5190.4 1987.22  5210.6 1993.90  5242.7 1986.69
  5341.2 1985.03  5439.6 1985.50  5478.8 1985.62  5734.9 1986.58  5735.0 1986.58
  6115.0 1987.09  6338.6 1987.32  6670.3 1987.64  6920.9 1988.21  7097.1 1992.77
#Mann=17,-1,0
  3756.8    0.07       0  4068.9   0.035       0  4475.1    0.07       0
  4513.5    0.16       0  4977.5    0.07       0  5008.4    0.16       0
  5132.9    0.07       0  5242.7   0.035       0  5341.2    0.07       0
  5439.6   0.035       0  5478.8    0.07       0  5734.9    0.05       0
  5735.0   0.035       0  6115.0    0.05       0  6338.6    0.07       0
  6670.3    0.05       0  6920.9    0.07       0
Bank Sta=4977.5,5008.4
Exp/Cntr=0.3,0.1

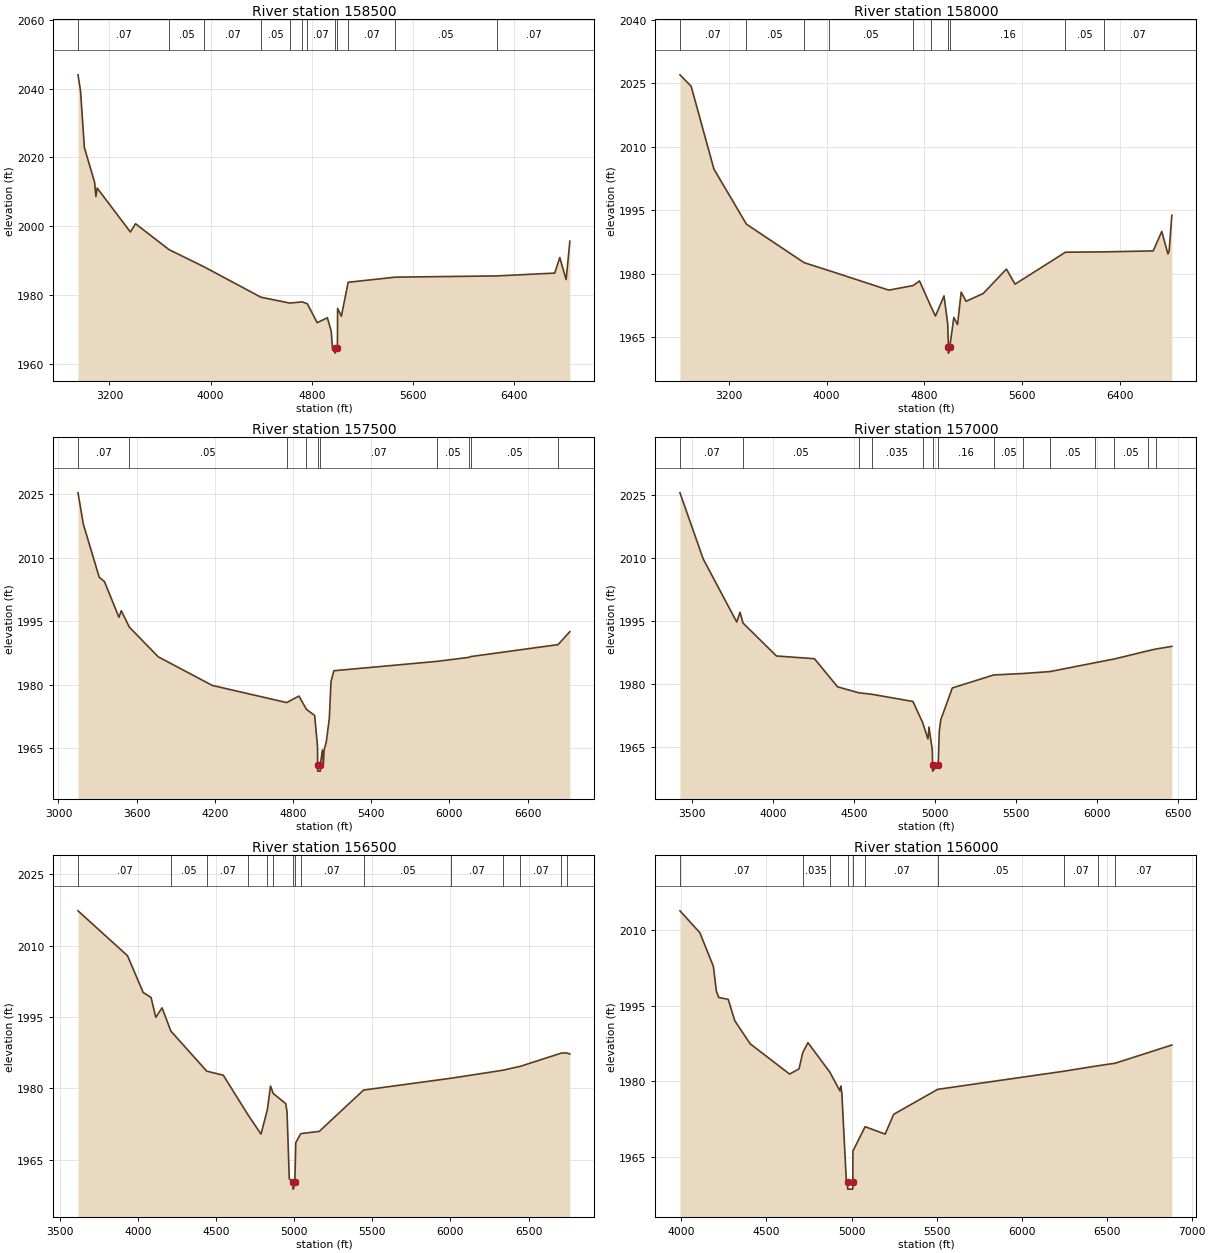
Type RM Length L Ch R = 1,158500,500,500,500
BEGIN DESCRIPTION:
Sweetwater Creek 316.0
END DESCRIPTION:
XS GIS Cut Line= 4
      1404093.58      6876417.84      1404404.42      6874392.56
      1404406.93      6873856.57      1404554.52      6872558.83
#Sta/Elev= 30
  2951.0 2044.00  2971.1 2039.28  3001.4 2022.86  3082.4 2012.74  3092.5 2008.61
  3102.6 2011.06  3365.6 1998.28  3406.1 2000.68  3671.0 1993.16  3945.8 1988.20
  4398.5 1979.31  4626.1 1977.61  4724.8 1977.95  4765.0 1977.42  4843.4 1971.91
  4923.7 1973.34  4954.0 1969.49  4964.1 1964.45  4982.5 1964.45  4982.8 1963.05
  5003.1 1964.45  5004.8 1976.04  5034.6 1973.81  5088.2 1983.66  5462.5 1985.15
  6265.8 1985.51  6722.2 1986.33  6762.4 1990.85  6812.7 1984.43  6842.1 1995.61
#Mann=12,-1,0
  2951.0    0.07       0  3671.0    0.05       0  3945.8    0.07       0
  4398.5    0.05       0  4626.1    0.07       0  4724.8    0.12       0
  4765.0    0.07       0  4982.5   0.035       0  5003.1    0.07       0
  5088.2    0.07       0  5462.5    0.05       0  6265.8    0.07       0
Bank Sta=4982.5,5003.1
Exp/Cntr=0.3,0.1

Type RM Length L Ch R = 1,158000,500,500,500
BEGIN DESCRIPTION:
Sweetwater Creek 315.0
END DESCRIPTION:
XS GIS Cut Line= 3
      1404695.83      6876629.00      1404887.41      6874438.07
      1404854.84      6872615.86
#Sta/Elev= 30
  2800.7 2027.04  2892.1 2024.34  3078.0 2004.77  3344.1 1991.72  3816.2 1982.61
  4021.0 1980.72  4508.2 1976.12  4707.7 1977.20  4759.2 1978.30  4852.1 1972.28
  4889.6 1969.99  4959.9 1974.76  4990.0 1968.08  4995.9 1962.62  4996.0 1961.22
  5006.2 1962.62  5040.1 1969.66  5070.1 1967.98  5100.1 1975.65  5140.1 1973.48
  5280.1 1975.32  5470.1 1981.10  5540.2 1977.53  5953.0 1985.09  6271.5 1985.17
  6670.3 1985.40  6740.3 1990.01  6790.4 1984.69  6800.4 1985.34  6822.5 1993.83
#Mann=10,-1,0
  2800.7    0.07       0  3344.1    0.05       0  3816.2    0.07       0
  4021.0    0.05       0  4707.7   0.035       0  4852.1    0.16       0
  4995.9    0.07       0  5006.2    0.16       0  5953.0    0.05       0
  6271.5    0.07       0
Bank Sta=4995.9,5006.2
Exp/Cntr=0.3,0.1

Type RM Length L Ch R = 1,157500,500,500,500
BEGIN DESCRIPTION:
Sweetwater Creek 314.0
END DESCRIPTION:
XS GIS Cut Line= 5
      1404822.85      6876508.97      1405052.89      6874891.19
      1405154.41      6874700.82      1405211.31      6874580.44
      1405539.16      6872818.74
#Sta/Elev= 30
  3150.2 2025.26  3191.6 2017.83  3312.8 2005.36  3353.2 2004.33  3464.3 1995.90
  3482.3 1997.45  3544.1 1993.58  3765.8 1986.58  4181.4 1979.82  4751.9 1975.78
  4846.0 1977.32  4903.2 1974.19  4966.5 1972.74  4988.4 1965.41  4989.4 1961.01
  4989.7 1959.61  5009.8 1959.61  5010.1 1961.01  5025.2 1964.57  5033.6 1961.42
  5039.2 1964.65  5056.4 1966.61  5079.2 1972.14  5091.6 1980.69  5113.7 1983.29
  5902.1 1985.49  6150.6 1986.45  6163.6 1986.63  6834.6 1989.45  6925.1 1992.51
#Mann=10,-1,0
  3150.2    0.07       0  3544.1    0.05       0  4751.9   0.035       0
  4903.2    0.07       0  4989.4    0.07       0  5010.1    0.07       0
  5902.1    0.05       0  6150.6    0.07       0  6163.6    0.05       0
  6834.6    0.07       0
Bank Sta=4989.4,5010.1
Exp/Cntr=0.3,0.1

Type RM Length L Ch R = 1,157000,500,500,500
BEGIN DESCRIPTION:
Sweetwater Creek 313.0
END DESCRIPTION:
XS GIS Cut Line= 5
      1405020.39      6876551.24      1405304.36      6875177.71
      1405437.06      6875069.97      1405492.11      6874985.03
      1405747.23      6873646.24
#Sta/Elev= 30
  3426.5 2025.46  3570.2 2009.69  3777.0 1994.70  3797.4 1997.04  3815.7 1994.46
  4022.2 1986.61  4256.9 1985.96  4399.9 1979.26  4531.6 1977.84  4609.9 1977.50
  4865.2 1975.78  4924.8 1970.78  4957.9 1966.84  4964.3 1969.68  4985.1 1964.16
  4986.6 1960.59  4987.0 1959.19  5017.6 1960.59  5022.0 1961.63  5028.0 1968.70
  5037.2 1971.43  5108.4 1979.00  5363.9 1982.09  5546.5 1982.44  5712.5 1982.90
  5989.0 1985.00  6109.5 1985.90  6314.4 1987.82  6365.3 1988.26  6464.1 1988.90
#Mann=14,-1,0
  3426.5    0.07       0  3815.7    0.05       0  4531.6    0.07       0
  4609.9   0.035       0  4924.8    0.16       0  4986.6    0.07       0
  5017.6    0.16       0  5363.9    0.05       0  5546.5    0.07       0
  5712.5    0.05       0  5989.0    0.07       0  6109.5    0.05       0
  6314.4    0.07       0  6365.3    0.05       0
Bank Sta=4986.6,5017.6
Exp/Cntr=0.3,0.1

Type RM Length L Ch R = 1,156500,500,500,500
BEGIN DESCRIPTION:
Sweetwater Creek 312.0
END DESCRIPTION:
XS GIS Cut Line= 5
      1405256.52      6876813.12      1405392.13      6875572.24
      1405498.48      6875485.50      1405631.10      6875383.40
      1405867.34      6873803.43
#Sta/Elev= 30
  3614.5 2017.35  3931.5 2007.91  4032.1 2000.17  4082.4 1999.14  4112.6 1994.96
  4152.8 1996.95  4209.6 1992.05  4438.9 1983.64  4545.1 1982.78  4705.0 1974.37
  4786.6 1970.41  4827.1 1975.50  4847.6 1980.50  4865.2 1978.94  4945.5 1976.79
  4953.4 1975.05  4967.8 1961.00  4993.0 1960.23  4993.2 1958.83  5003.4 1960.23
  5009.3 1968.58  5041.1 1970.50  5159.7 1970.97  5443.6 1979.66  6004.1 1982.15
  6335.7 1983.83  6447.4 1984.65  6710.6 1987.44  6745.3 1987.47  6764.9 1987.23
#Mann=15,-1,0
  3614.5    0.07       0  4209.6    0.05       0  4438.9    0.07       0
  4705.0   0.035       0  4827.1    0.07       0  4865.2   0.035       0
  4993.0   0.035       0  5003.4   0.035       0  5041.1    0.07       0
  5443.6    0.05       0  6004.1    0.07       0  6335.7    0.05       0
  6447.4    0.07       0  6710.6    0.05       0  6745.3    0.07       0
Bank Sta=4993,5003.4
Exp/Cntr=0.3,0.1

Type RM Length L Ch R = 1,156000,500,500,500
BEGIN DESCRIPTION:
Sweetwater Creek 311.0
END DESCRIPTION:
XS GIS Cut Line= 4
      1405524.92      6876725.39      1405829.25      6875763.70
      1405867.36      6875493.46      1405950.92      6873885.14
#Sta/Elev= 30
  3991.3 2013.81  4108.4 2009.47  4187.9 2002.79  4205.3 1997.89  4219.3 1996.64
  4275.1 1996.27  4313.7 1992.02  4404.4 1987.45  4635.8 1981.47  4691.3 1982.49
  4713.0 1985.70  4743.8 1987.69  4872.4 1981.85  4931.7 1978.13  4937.0 1979.10
  4943.0 1977.72  4969.3 1960.42  4976.8 1960.07  4977.3 1958.67  5007.4 1958.67
  5007.9 1960.07  5008.1 1966.21  5079.9 1971.04  5197.6 1969.57  5248.1 1973.50
  5506.6 1978.44  6246.7 1982.02  6451.7 1983.13  6549.6 1983.61  6883.4 1987.22
#Mann=10,-1,0
  3991.3    0.07       0  4713.0   0.035       0  4872.4    0.07       0
  4976.8    0.07       0  5007.9    0.07       0  5079.9    0.07       0
  5506.6    0.05       0  6246.7    0.07       0  6451.7    0.05       0
  6549.6    0.07       0
Bank Sta=4976.8,5007.9
Exp/Cntr=0.3,0.1

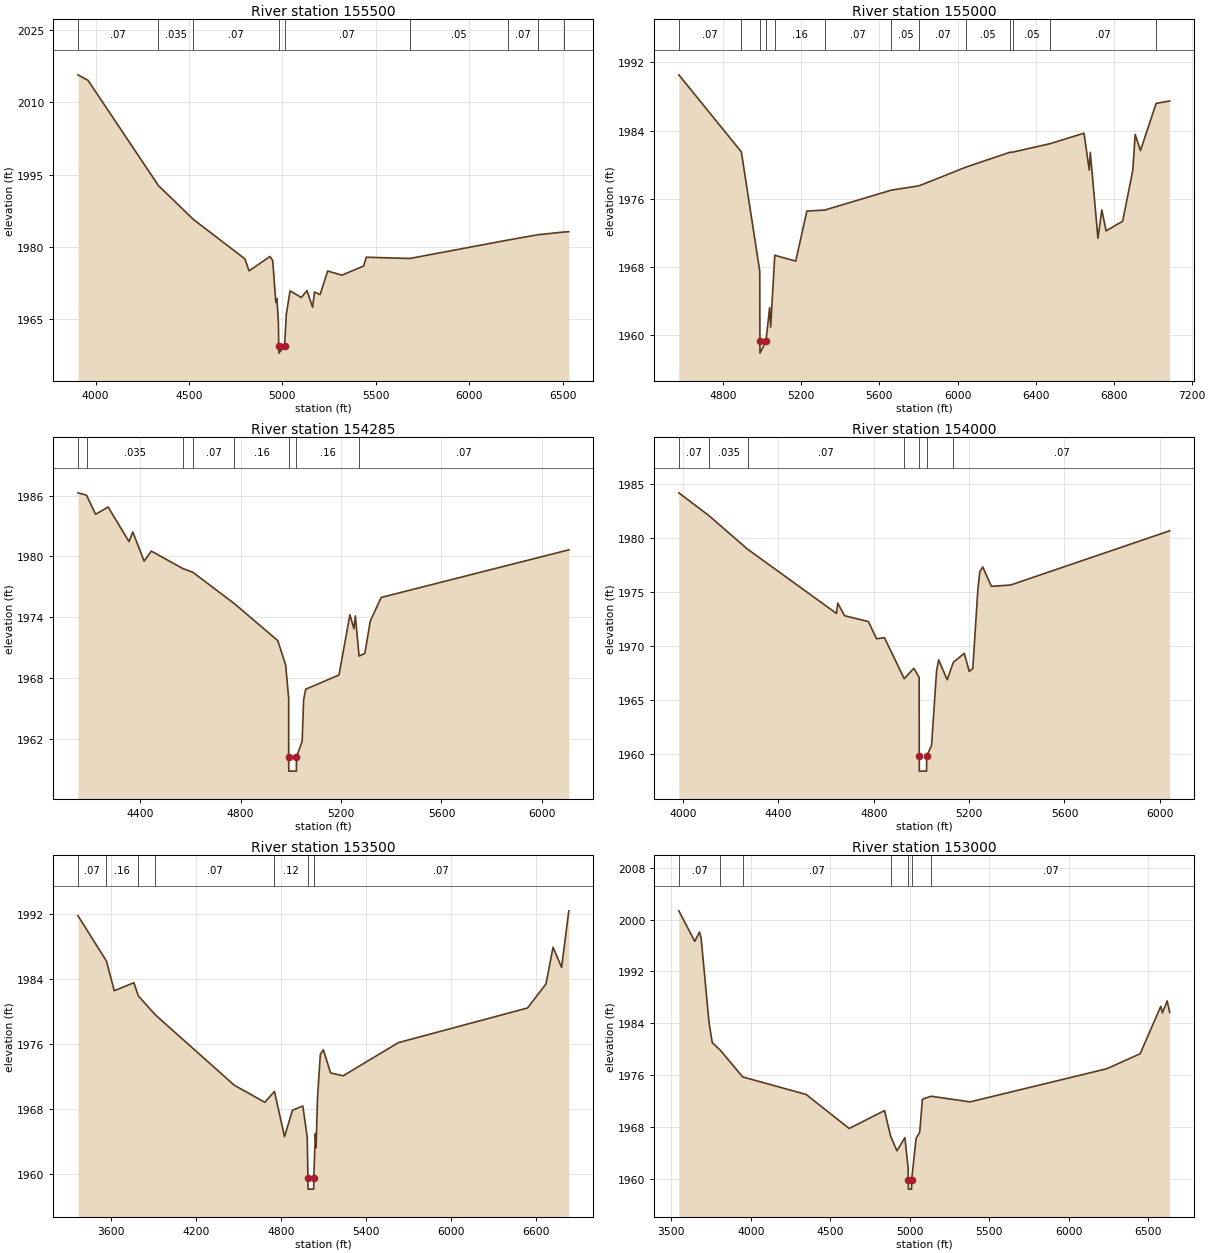
Type RM Length L Ch R = 1,155500,500,500,500
BEGIN DESCRIPTION:
Sweetwater Creek 310.0
END DESCRIPTION:
XS GIS Cut Line= 4
      1405737.22      6876783.97      1406234.40      6875809.14
      1406256.49      6875597.52      1406051.96      6874292.51
#Sta/Elev= 30
  3905.7 2015.69  3959.4 2014.55  4336.5 1992.71  4522.7 1985.72  4799.2 1977.51
  4821.7 1975.01  4933.9 1977.99  4948.5 1977.14  4965.1 1968.43  4970.8 1969.28
  4978.8 1964.39  4980.7 1959.34  4981.2 1957.94  5011.7 1959.34  5021.2 1965.96
  5041.4 1970.87  5101.7 1969.48  5131.8 1970.92  5162.0 1967.45  5172.1 1970.62
  5202.2 1970.08  5242.6 1974.98  5318.9 1974.12  5435.0 1976.01  5449.3 1977.84
  5682.6 1977.58  6207.5 1981.40  6367.4 1982.50  6506.1 1983.07  6533.7 1983.13
#Mann=9,-1,0
  3905.7    0.07       0  4336.5   0.035       0  4522.7    0.07       0
  4980.7    0.07       0  5011.7    0.07       0  5682.6    0.05       0
  6207.5    0.07       0  6367.4    0.05       0  6506.1    0.07       0
Bank Sta=4980.7,5011.7
Exp/Cntr=0.3,0.1

Type RM Length L Ch R = 1,155000,715,715,715
BEGIN DESCRIPTION:
Sweetwater Creek 309.0
END DESCRIPTION:
XS GIS Cut Line= 3
      1406754.99      6876237.98      1406642.53      6875825.33
      1406005.00      6873837.99
#Sta/Elev= 30
  4572.3 1990.55  4892.6 1981.51  4986.9 1967.51  4987.7 1959.29  4988.1 1957.89
  5018.7 1959.29  5037.5 1963.23  5042.7 1960.93  5063.8 1969.37  5171.2 1968.69
  5228.2 1974.56  5319.8 1974.68  5661.6 1977.02  5803.7 1977.53  6044.7 1979.73
  6266.9 1981.45  6283.4 1981.48  6474.3 1982.47  6648.2 1983.70  6675.1 1979.36
  6680.3 1981.46  6719.5 1971.38  6739.3 1974.69  6761.5 1972.24  6846.2 1973.37
  6898.1 1979.35  6910.4 1983.55  6937.3 1981.66  7017.8 1987.20  7087.1 1987.48
#Mann=13,-1,0
  4572.3    0.07       0  4892.6    0.16       0  4987.7    0.07       0
  5018.7    0.16       0  5063.8    0.16       0  5319.8    0.07       0
  5661.6    0.05       0  5803.7    0.07       0  6044.7    0.05       0
  6266.9    0.07       0  6283.4    0.05       0  6474.3    0.07       0
  7017.8    0.05       0
Bank Sta=4987.7,5018.7
Exp/Cntr=0.3,0.1

Type RM Length L Ch R = 1,154285,285,285,285
BEGIN DESCRIPTION:
Sweetwater Creek 308.0
END DESCRIPTION:
XS GIS Cut Line= 3
      1407593.75      6876232.30      1407247.60      6875559.54
      1406666.87      6874511.46
#Sta/Elev= 30
  4152.3 1986.27  4186.4 1986.04  4222.5 1984.15  4272.5 1984.87  4355.6 1981.45
  4370.8 1982.40  4415.8 1979.53  4444.3 1980.52  4570.2 1978.79  4610.2 1978.42
  4775.2 1975.33  4947.9 1971.68  4979.2 1969.31  4991.4 1966.01  4991.5 1960.19
  4991.9 1958.79  5022.2 1958.79  5022.6 1960.19  5045.2 1961.74  5051.0 1965.83
  5059.3 1966.88  5191.8 1968.28  5235.3 1974.23  5251.3 1972.85  5257.0 1974.12
  5271.9 1970.15  5294.8 1970.41  5316.5 1973.61  5360.0 1975.94  6107.1 1980.64
#Mann=8,-1,0
  4152.3    0.07       0  4186.4   0.035       0  4570.2    0.16       0
  4610.2    0.07       0  4775.2    0.16       0  4991.5    0.07       0
  5022.6    0.16       0  5271.9    0.07       0
Bank Sta=4991.5,5022.6
Exp/Cntr=0.3,0.1

Type RM Length L Ch R = 1,154000,500,500,500
BEGIN DESCRIPTION:
Sweetwater Creek 307.0
END DESCRIPTION:
XS GIS Cut Line= 3
      1407797.90      6876159.55      1407343.04      6875249.60
      1406751.72      6874392.61
#Sta/Elev= 30
  3982.7 1984.17  4109.7 1982.04  4272.0 1978.93  4643.7 1972.99  4649.3 1973.94
  4677.6 1972.78  4777.9 1972.23  4811.7 1970.64  4845.0 1970.74  4927.8 1966.94
  4968.3 1967.90  4990.6 1967.06  4990.9 1959.77  4991.3 1958.37  5021.6 1958.37
  5022.1 1959.77  5042.5 1960.74  5063.5 1967.63  5072.3 1968.69  5108.1 1966.84
  5133.9 1968.46  5179.8 1969.29  5200.7 1967.61  5215.6 1967.88  5236.6 1975.15
  5244.9 1976.86  5257.5 1977.29  5293.5 1975.50  5373.8 1975.62  6041.2 1980.65
#Mann=7,-1,0
  3982.7    0.07       0  4109.7   0.035       0  4272.0    0.07       0
  4927.8    0.12       0  4990.9    0.07       0  5022.1    0.12       0
  5133.9    0.07       0
Bank Sta=4990.9,5022.1
Exp/Cntr=0.3,0.1

Type RM Length L Ch R = 1,153500,500,500,500
BEGIN DESCRIPTION:
Sweetwater Creek 306.0
END DESCRIPTION:
XS GIS Cut Line= 4
      1408051.01      6876543.05      1407590.84      6874973.30
      1407488.94      6874585.69      1407599.16      6873157.02
#Sta/Elev= 30
  3364.2 1991.74  3565.6 1986.16  3620.7 1982.51  3759.5 1983.50  3790.5 1981.89
  3911.0 1979.55  4469.3 1970.89  4685.4 1968.79  4753.1 1970.13  4824.2 1964.57
  4880.5 1967.81  4953.4 1968.34  4984.7 1964.52  4989.7 1959.51  4990.3 1958.11
  5030.6 1958.11  5031.2 1959.51  5042.2 1964.95  5047.3 1963.22  5057.2 1969.21
  5077.3 1974.68  5098.5 1975.25  5150.2 1972.40  5238.7 1972.05  5629.2 1976.13
  6541.9 1980.39  6672.2 1983.34  6722.4 1987.86  6782.6 1985.38  6833.7 1992.34
#Mann=7,-1,0
  3364.2    0.07       0  3565.6    0.16       0  3790.5   0.035       0
  3911.0    0.07       0  4753.1    0.12       0  4989.7    0.07       0
  5031.2    0.07       0
Bank Sta=4989.7,5031.2
Exp/Cntr=0.3,0.1

Type RM Length L Ch R = 1,153000,500,500,500
BEGIN DESCRIPTION:
Sweetwater Creek 305.0
END DESCRIPTION:
XS GIS Cut Line= 3
      1408155.00      6876388.00      1408070.64      6874938.05
      1408053.58      6873302.24
#Sta/Elev= 30
  3547.6 2001.34  3647.8 1996.63  3677.8 1998.07  3687.8 1997.13  3737.9 1984.02
  3758.0 1980.99  3809.1 1979.81  3949.4 1975.70  4349.0 1972.99  4619.4 1967.74
  4841.8 1970.51  4879.9 1966.56  4919.9 1964.29  4970.0 1966.33  4990.0 1961.68
  4991.6 1959.78  4991.9 1958.38  5012.1 1958.38  5012.4 1959.78  5040.1 1966.18
  5063.0 1967.16  5080.1 1972.25  5134.1 1972.72  5380.1 1971.85  6240.1 1976.96
  6450.1 1979.28  6580.1 1986.60  6590.1 1985.59  6620.1 1987.43  6635.9 1985.67
#Mann=7,-1,0
  3547.6    0.07       0  3809.1   0.035       0  3949.4    0.07       0
  4879.9    0.12       0  4991.6    0.07       0  5012.4    0.12       0
  5134.1    0.07       0
Bank Sta=4991.6,5012.4
Exp/Cntr=0.3,0.1

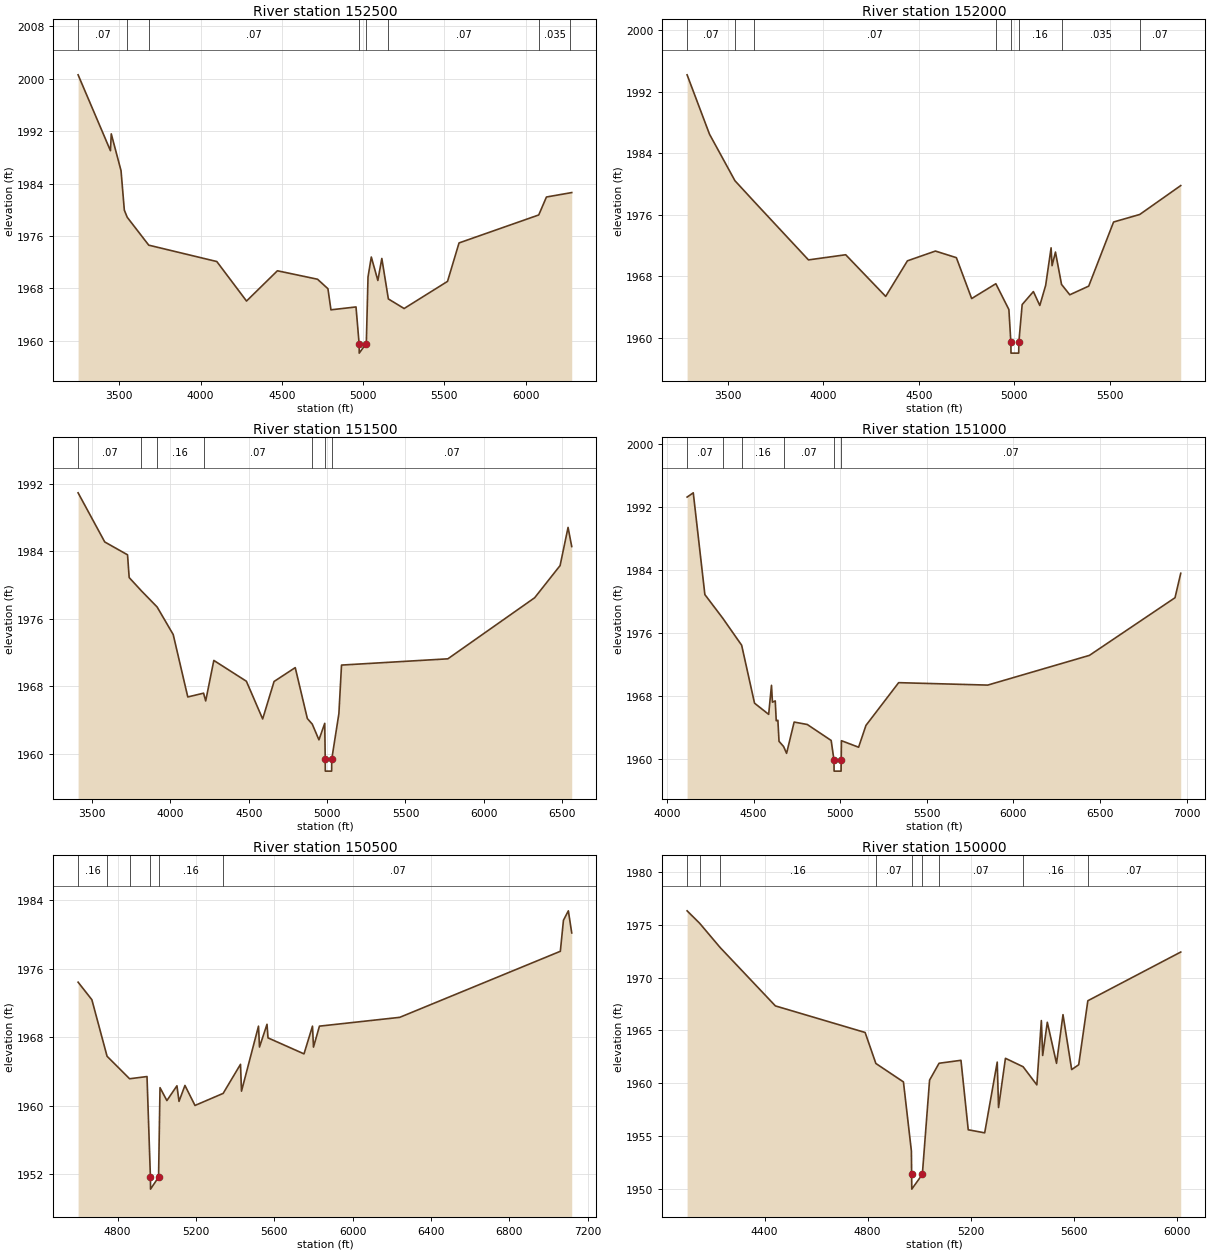
Type RM Length L Ch R = 1,152500,500,500,500
BEGIN DESCRIPTION:
Sweetwater Creek 304.0
END DESCRIPTION:
XS GIS Cut Line= 5
      1408255.00      6876387.99      1408515.88      6874921.15
      1408415.23      6874678.02      1408371.00      6874348.78
      1409054.97      6873688.03
#Sta/Elev= 30
  3247.0 2000.61  3446.0 1989.03  3451.0 1991.60  3511.1 1985.98  3531.4 1979.95
  3549.4 1978.86  3681.6 1974.61  4100.2 1972.11  4283.0 1966.08  4472.9 1970.70
  4719.7 1969.41  4783.7 1967.96  4802.2 1964.74  4956.4 1965.18  4975.6 1959.53
  4976.2 1958.13  5017.2 1959.53  5020.2 1960.01  5030.3 1969.77  5050.5 1972.80
  5090.8 1969.22  5115.2 1972.58  5155.4 1966.40  5252.3 1964.94  5519.3 1969.08
  5590.1 1974.95  6080.4 1979.22  6127.7 1981.96  6274.5 1982.60  6283.2 1982.64
#Mann=8,-1,0
  3247.0    0.07       0  3549.4   0.035       0  3681.6    0.07       0
  4975.6    0.07       0  5017.2    0.07       0  5155.4    0.07       0
  6080.4   0.035       0  6274.5   0.063       0
Bank Sta=4975.6,5017.2
Exp/Cntr=0.3,0.1

Type RM Length L Ch R = 1,152000,500,500,500
BEGIN DESCRIPTION:
Sweetwater Creek 303.0
END DESCRIPTION:
XS GIS Cut Line= 3
      1408423.93      6876391.13      1408868.07      6874738.16
      1409055.01      6873887.97
#Sta/Elev= 30
  3288.4 1994.22  3405.5 1986.50  3538.7 1980.44  3639.4 1977.72  3923.2 1970.14
  4118.0 1970.81  4327.1 1965.39  4441.0 1970.02  4587.3 1971.29  4696.9 1970.43
  4776.9 1965.11  4903.4 1967.04  4971.6 1963.68  4982.0 1959.41  4982.6 1958.01
  5023.0 1958.01  5023.6 1959.41  5041.1 1964.33  5099.8 1966.02  5133.3 1964.21
  5164.0 1966.83  5192.4 1971.71  5197.5 1969.39  5215.2 1971.16  5247.0 1966.95
  5290.2 1965.60  5389.2 1966.73  5519.2 1975.07  5656.1 1976.05  5870.5 1979.81
#Mann=8,-1,0
  3288.4    0.07       0  3538.7   0.035       0  3639.4    0.07       0
  4903.4    0.16       0  4982.0    0.07       0  5023.6    0.16       0
  5247.0   0.035       0  5656.1    0.07       0
Bank Sta=4982,5023.6
Exp/Cntr=0.3,0.1

Type RM Length L Ch R = 1,151500,500,500,500
BEGIN DESCRIPTION:
Sweetwater Creek 302.0
END DESCRIPTION:
XS GIS Cut Line= 5
      1408526.30      6876541.73      1408913.39      6875170.55
      1409054.92      6875086.27      1409227.68      6875019.67
      1409468.37      6873664.94
#Sta/Elev= 30
  3410.5 1990.90  3580.6 1985.09  3726.1 1983.57  3736.5 1980.88  3814.0 1979.32
  3914.9 1977.40  4017.6 1974.14  4110.6 1966.76  4211.4 1967.21  4224.9 1966.29
  4276.8 1971.08  4484.6 1968.62  4588.5 1964.16  4661.3 1968.59  4796.4 1970.23
  4873.7 1964.21  4905.0 1963.55  4947.7 1961.69  4984.7 1963.64  4987.8 1959.39
  4988.4 1957.99  5028.8 1957.99  5029.4 1959.39  5075.1 1964.80  5091.8 1970.53
  5770.5 1971.27  6324.4 1978.49  6486.9 1982.30  6537.7 1986.81  6561.1 1984.55
#Mann=7,-1,0
  3410.5    0.07       0  3814.0   0.035       0  3914.9    0.16       0
  4211.4    0.07       0  4905.0    0.16       0  4987.8    0.07       0
  5029.4    0.07       0
Bank Sta=4987.8,5029.4
Exp/Cntr=0.3,0.1

Type RM Length L Ch R = 1,151000,500,500,500
BEGIN DESCRIPTION:
Sweetwater Creek 301.0
END DESCRIPTION:
XS GIS Cut Line= 4
      1408705.00      6876338.00      1409128.91      6875562.50
      1409244.78      6875447.45      1409674.33      6873695.94
#Sta/Elev= 30
  4116.2 1993.28  4151.8 1993.82  4218.8 1980.88  4321.3 1977.90  4431.2 1974.44
  4505.6 1967.07  4587.2 1965.65  4603.4 1969.34  4609.0 1967.20  4625.2 1967.36
  4630.9 1964.83  4640.4 1964.90  4647.0 1962.22  4673.4 1961.56  4690.6 1960.69
  4734.3 1964.67  4810.2 1964.36  4948.1 1962.33  4964.4 1959.83  4965.0 1958.43
  5005.4 1958.43  5006.0 1959.83  5007.5 1962.30  5106.5 1961.47  5148.9 1964.24
  5337.8 1969.68  5852.2 1969.37  6439.5 1973.15  6933.7 1980.48  6966.7 1983.59
#Mann=6,-1,0
  4116.2    0.07       0  4321.3   0.035       0  4431.2    0.16       0
  4673.4    0.07       0  4964.4    0.07       0  5006.0    0.07       0
Bank Sta=4964.4,5006
Exp/Cntr=0.3,0.1

Type RM Length L Ch R = 1,150500,500,500,500
BEGIN DESCRIPTION:
Sweetwater Creek 300.0
END DESCRIPTION:
XS GIS Cut Line= 3
      1409405.00      6876187.95      1409446.29      6875788.08
      1409909.11      6873721.26
#Sta/Elev= 30
  4598.0 1974.42  4668.3 1972.37  4745.9 1965.76  4860.9 1963.13  4949.8 1963.39
  4967.2 1951.63  4967.8 1950.23  5008.8 1951.63  5016.2 1962.09  5051.3 1960.58
  5102.6 1962.31  5113.2 1960.49  5143.5 1962.35  5194.8 1960.01  5338.5 1961.42
  5427.1 1964.82  5432.2 1961.68  5519.0 1969.28  5524.1 1966.84  5562.4 1969.50
  5567.5 1967.91  5751.2 1966.04  5794.6 1969.28  5799.7 1966.83  5830.1 1969.28
  6240.0 1970.31  7059.9 1978.03  7075.8 1981.66  7100.8 1982.76  7118.0 1980.18
#Mann=6,-1,0
  4598.0    0.16       0  4745.9    0.07       0  4860.9    0.16       0
  4967.2    0.07       0  5008.8    0.16       0  5338.5    0.07       0
Bank Sta=4967.2,5008.8
Exp/Cntr=0.3,0.1

Type RM Length L Ch R = 1,150000,500,500,500
BEGIN DESCRIPTION:
Sweetwater Creek 299.0
END DESCRIPTION:
XS GIS Cut Line= 3
      1409572.99      6876325.89      1409725.82      6875438.26
      1409905.00      6874437.98
#Sta/Elev= 30
  4099.3 1976.35  4148.4 1975.16  4227.2 1972.88  4442.2 1967.33  4790.6 1964.81
  4832.3 1961.87  4939.4 1960.12  4970.3 1953.56  4971.2 1951.35  4971.8 1949.95
  5012.8 1951.35  5040.9 1960.29  5077.7 1961.89  5162.8 1962.17  5191.0 1955.58
  5254.9 1955.29  5303.6 1962.00  5308.7 1957.69  5335.5 1962.36  5404.1 1961.56
  5457.4 1959.84  5475.0 1965.94  5480.1 1962.63  5498.1 1965.78  5533.9 1961.88
  5559.0 1966.50  5592.7 1961.29  5620.0 1961.75  5655.5 1967.82  6016.2 1972.44
#Mann=9,-1,0
  4099.3   0.035       0  4148.4    0.07       0  4227.2    0.16       0
  4832.3    0.07       0  4971.2    0.07       0  5012.8    0.07       0
  5077.7    0.07       0  5404.1    0.16       0  5655.5    0.07       0
Bank Sta=4971.2,5012.8
Exp/Cntr=0.3,0.1

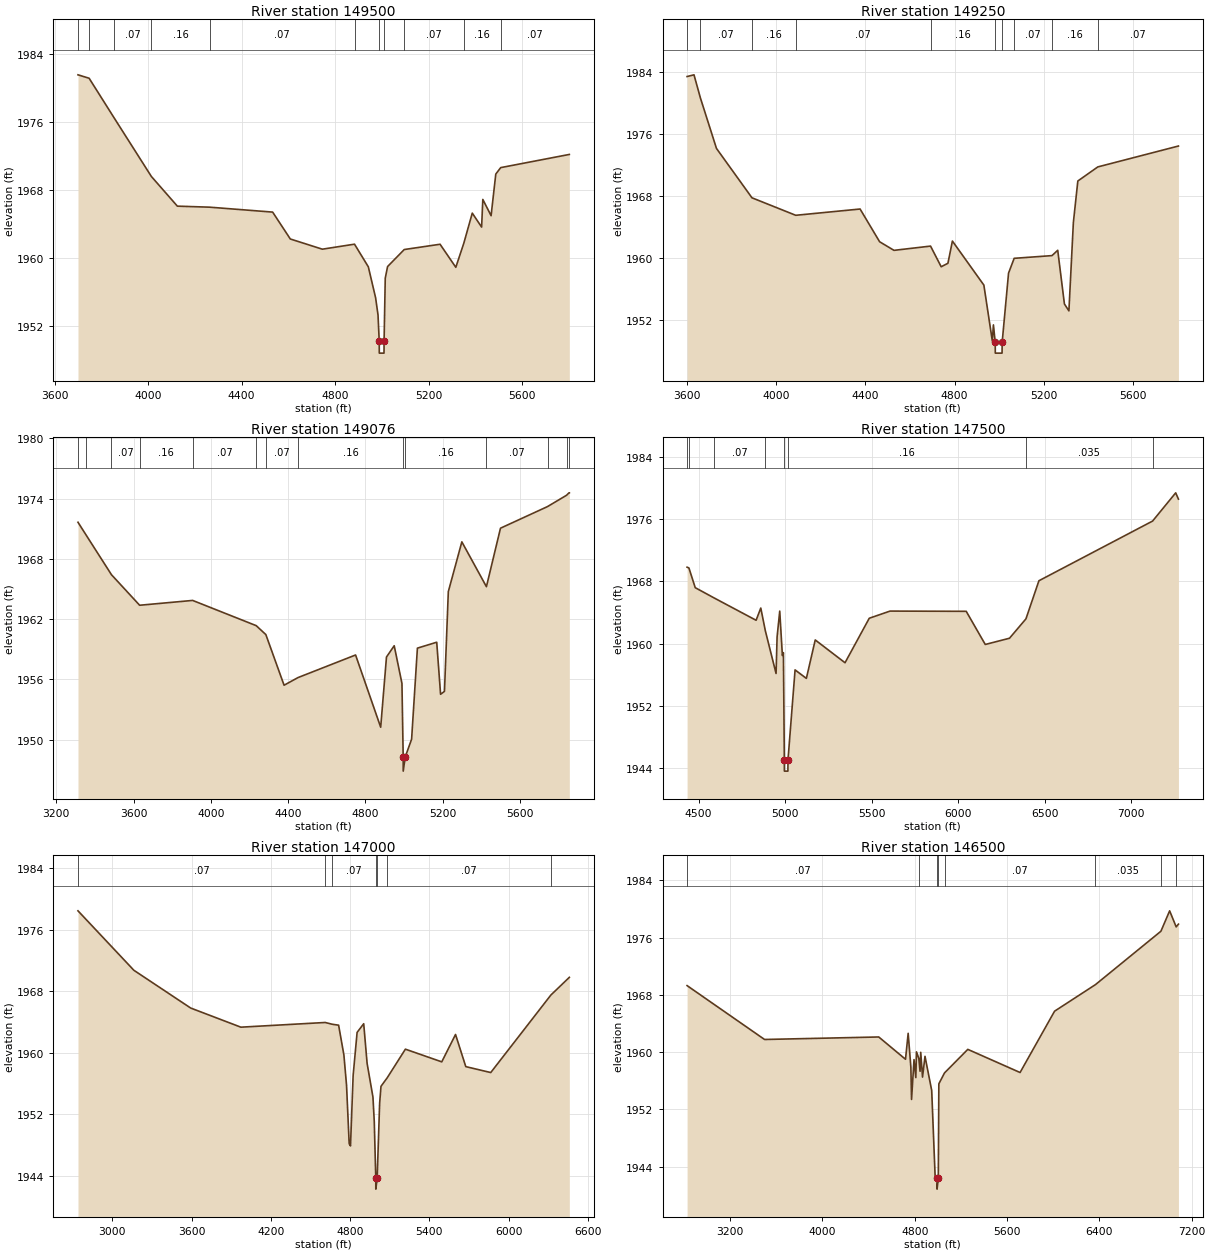
Type RM Length L Ch R = 1,149500,250,250,250
BEGIN DESCRIPTION:
Sweetwater Creek 298.0
END DESCRIPTION:
XS GIS Cut Line= 4
      1409744.87      6876423.69      1410208.61      6875411.38
      1410156.77      6875232.10      1410069.84      6874435.23
#Sta/Elev= 30
  3699.9 1981.57  3747.5 1981.17  3853.8 1976.54  4013.8 1969.62  4125.0 1966.13
  4262.8 1966.01  4532.6 1965.43  4608.1 1962.27  4745.1 1961.07  4882.7 1961.66
  4941.8 1959.00  4973.0 1955.35  4983.3 1953.33  4988.4 1950.25  4988.7 1948.85
  5008.9 1948.85  5009.2 1950.25  5014.2 1957.66  5024.2 1959.03  5095.5 1961.03
  5248.7 1961.65  5316.0 1958.94  5350.1 1961.76  5386.4 1965.31  5426.4 1963.67
  5431.5 1966.92  5466.9 1965.01  5487.0 1969.90  5508.0 1970.66  5801.6 1972.21
#Mann=11,-1,0
  3699.9    0.07       0  3747.5   0.035       0  3853.8    0.07       0
  4013.8    0.16       0  4262.8    0.07       0  4882.7    0.16       0
  4988.4    0.07       0  5009.2    0.16       0  5095.5    0.07       0
  5350.1    0.16       0  5508.0    0.07       0
Bank Sta=4988.4,5009.2
Exp/Cntr=0.3,0.1

Type RM Length L Ch R = 1,149250,174,174,174
BEGIN DESCRIPTION:
Sweetwater Creek 297.0
END DESCRIPTION:
XS GIS Cut Line= 3
      1410187.65      6876478.76      1410353.38      6875089.61
      1410305.00      6874287.97
#Sta/Elev= 30
  3601.0 1983.47  3632.0 1983.69  3660.7 1980.70  3732.7 1974.18  3891.8 1967.80
  4088.0 1965.54  4376.4 1966.35  4463.9 1962.12  4528.3 1961.01  4692.1 1961.56
  4739.8 1958.89  4770.0 1959.34  4790.1 1962.21  4931.1 1956.52  4968.9 1949.32
  4973.9 1951.38  4981.9 1949.13  4982.3 1947.73  5012.6 1947.73  5013.1 1949.13
  5041.7 1958.07  5066.9 1959.98  5236.4 1960.33  5262.1 1961.02  5292.1 1954.08
  5312.2 1953.19  5332.2 1964.61  5352.2 1969.97  5441.7 1971.79  5803.1 1974.49
#Mann=10,-1,0
  3601.0   0.035       0  3660.7    0.07       0  3891.8    0.16       0
  4088.0    0.07       0  4692.1    0.16       0  4981.9    0.07       0
  5013.1    0.16       0  5066.9    0.07       0  5236.4    0.16       0
  5441.7    0.07       0
Bank Sta=4981.9,5013.1
Exp/Cntr=0.3,0.1

Type RM Length L Ch R = 1,149076,1576,1576,1576
BEGIN DESCRIPTION:
Sweetwater Creek 295.0
END DESCRIPTION:
XS GIS Cut Line= 5
      1410405.19      6876632.13      1410508.93      6876526.54
      1410521.63      6876140.21      1410471.45      6874419.91
      1410516.43      6874135.14
#Sta/Elev= 30
  3312.0 1971.65  3354.7 1970.36  3485.4 1966.43  3631.2 1963.39  3905.7 1963.87
  4234.7 1961.36  4284.7 1960.47  4379.0 1955.43  4451.0 1956.19  4749.2 1958.44
  4879.2 1951.25  4909.2 1958.24  4949.2 1959.36  4989.3 1955.61  4995.7 1948.28
  4995.9 1946.88  5006.1 1948.28  5039.3 1950.06  5069.3 1959.12  5169.3 1959.71
  5189.3 1954.53  5209.4 1954.82  5229.4 1964.75  5299.4 1969.70  5426.6 1965.24
  5499.5 1971.06  5742.9 1973.21  5841.6 1974.34  5854.2 1974.58  5855.9 1974.58
#Mann=14,-1,0
  3312.0    0.07       0  3354.7   0.035       0  3485.4    0.07       0
  3631.2    0.16       0  3905.7    0.07       0  4234.7    0.16       0
  4284.7    0.07       0  4451.0    0.16       0  4995.7    0.07       0
  5006.1    0.16       0  5426.6    0.07       0  5742.9   0.035       0
  5841.6    0.07       0  5854.2   0.035       0
Bank Sta=4995.7,5006.1
Exp/Cntr=0.3,0.1

Type RM Length L Ch R = 1,147500,500,500,500
BEGIN DESCRIPTION:
Sweetwater Creek 294.0
END DESCRIPTION:
XS GIS Cut Line= 5
      1410474.19      6876622.41      1410771.52      6876405.98
      1410877.23      6876238.04      1410934.37      6875980.68
      1410981.91      6873972.17
#Sta/Elev= 30
  4433.8 1969.82  4444.3 1969.73  4480.9 1967.19  4586.6 1965.91  4832.5 1963.00
  4859.6 1964.57  4886.0 1961.64  4947.9 1956.16  4953.8 1960.86  4969.1 1964.18
  4984.4 1958.47  4990.3 1958.84  4995.7 1945.01  4996.0 1943.61  5016.3 1943.61
  5016.6 1945.01  5057.7 1956.62  5123.0 1955.53  5174.2 1960.47  5346.3 1957.54
  5486.4 1963.26  5606.4 1964.18  6046.5 1964.15  6156.6 1959.89  6296.6 1960.69
  6391.6 1963.18  6466.6 1968.08  7123.3 1975.75  7256.9 1979.38  7272.7 1978.57
#Mann=8,-1,0
  4433.8    0.07       0  4444.3   0.035       0  4586.6    0.07       0
  4886.0    0.16       0  4995.7    0.07       0  5016.6    0.16       0
  6391.6   0.035       0  7123.3    0.07       0
Bank Sta=4995.7,5016.6
Exp/Cntr=0.3,0.1

Type RM Length L Ch R = 1,147000,500,500,500
BEGIN DESCRIPTION:
Sweetwater Creek 293.0
END DESCRIPTION:
XS GIS Cut Line= 3
      1411292.40      6878371.00      1411331.21      6876111.23
      1411005.01      6874688.04
#Sta/Elev= 30
  2739.9 1978.45  3163.0 1970.72  3593.0 1965.81  3973.1 1963.32  4611.7 1963.93
  4665.0 1963.70  4713.2 1963.58  4753.2 1959.71  4773.2 1955.78  4793.2 1948.18
  4803.2 1947.88  4823.2 1957.05  4853.2 1962.64  4903.2 1963.77  4929.0 1958.61
  4973.2 1954.23  4983.2 1951.03  4994.7 1943.66  4994.9 1942.26  5005.1 1943.66
  5023.8 1953.42  5034.1 1955.63  5081.7 1956.75  5218.8 1960.46  5494.2 1958.81
  5598.4 1962.37  5676.1 1958.19  5865.1 1957.42  6320.4 1967.50  6460.1 1969.80
#Mann=7,-1,0
  2739.9    0.07       0  4611.7    0.16       0  4665.0    0.07       0
  4994.7    0.07       0  5005.1    0.07       0  5081.7    0.07       0
  6320.4   0.035       0
Bank Sta=4994.7,5005.1
Exp/Cntr=0.3,0.1

Type RM Length L Ch R = 1,146500,500,500,500
BEGIN DESCRIPTION:
Sweetwater Creek 292.0
END DESCRIPTION:
XS GIS Cut Line= 6
      1411607.34      6877819.75      1411923.71      6875987.61
      1411654.63      6875825.29      1411534.91      6875802.93
      1411284.13      6875503.68      1411093.01      6873942.36
#Sta/Elev= 30
  2826.5 1969.29  3498.0 1961.77  4487.6 1962.12  4719.6 1959.01  4742.6 1962.63
  4766.0 1957.92  4772.0 1953.40  4793.3 1958.96  4808.9 1956.45  4814.7 1960.04
  4835.1 1959.13  4845.7 1957.33  4851.6 1959.98  4867.1 1956.52  4888.5 1959.42
  4946.7 1954.65  4976.2 1942.73  4993.0 1942.38  4993.1 1940.88  5003.8 1942.38
  5008.6 1955.58  5057.6 1957.10  5259.6 1960.39  5712.6 1957.16  6011.6 1965.72
  6366.1 1969.43  6933.3 1976.88  7009.0 1979.73  7065.6 1977.49  7085.2 1977.87
#Mann=8,-1,0
  2826.5    0.07       0  4835.1    0.16       0  4993.0    0.07       0
  5003.8    0.16       0  5057.6    0.07       0  6366.1   0.035       0
  6933.3    0.07       0  7065.6   0.035       0
Bank Sta=4993,5003.8
Exp/Cntr=0.3,0.1