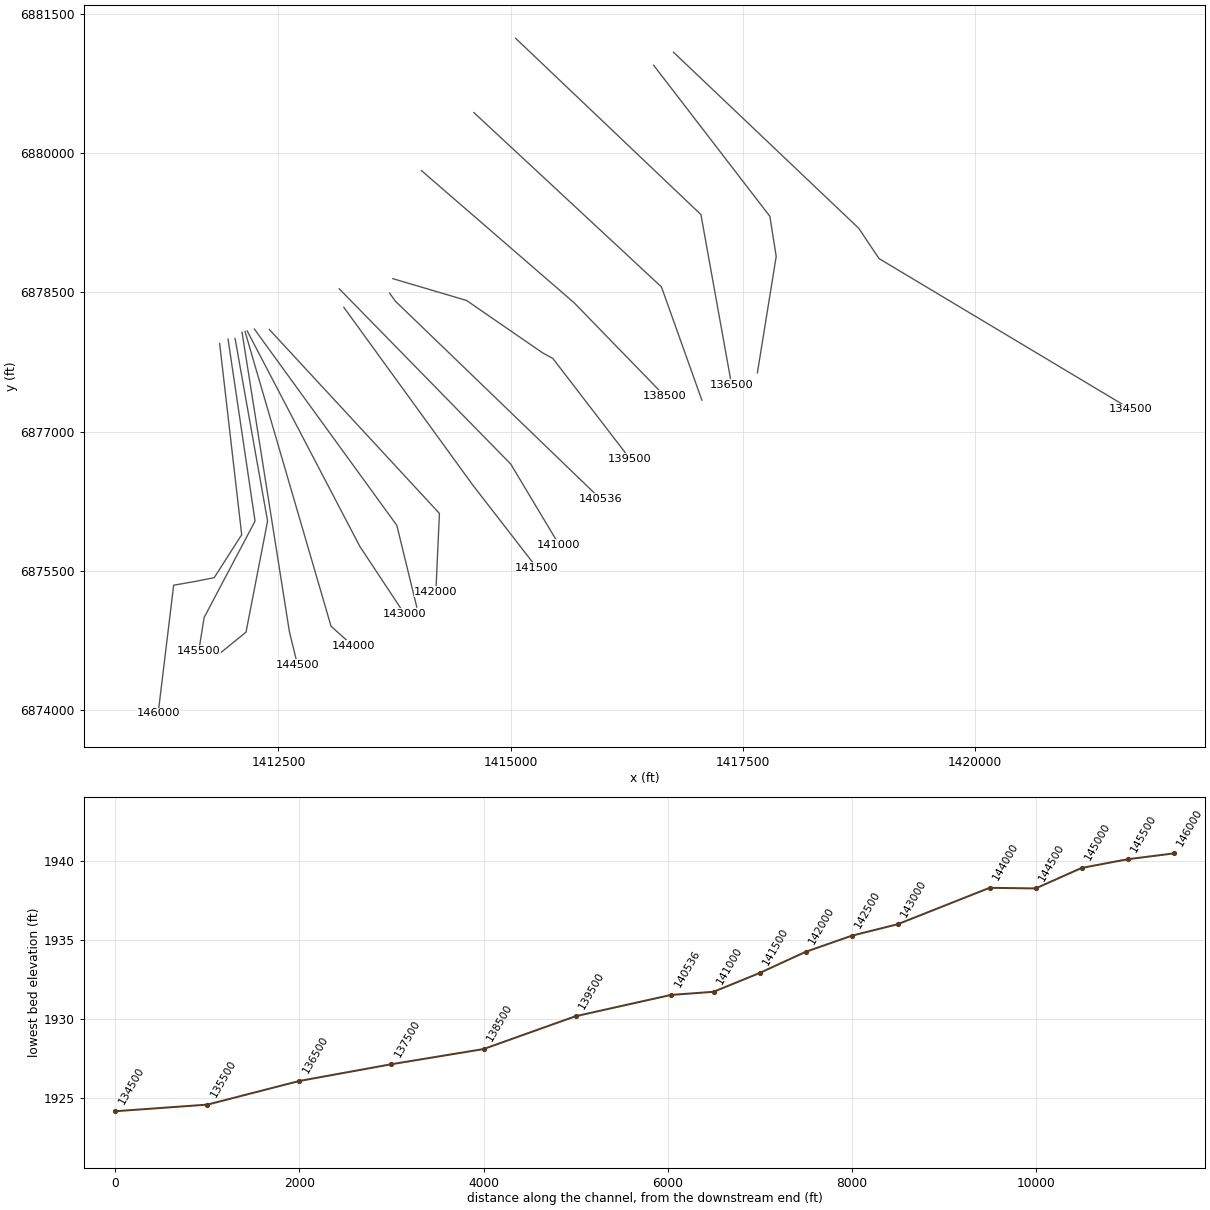
HEC-RAS study Sweetwater Creek.prj: Sweetwater Creek Base Level Engineering

--- Sweetwater Creek.g01 (geometry) --- (continued)

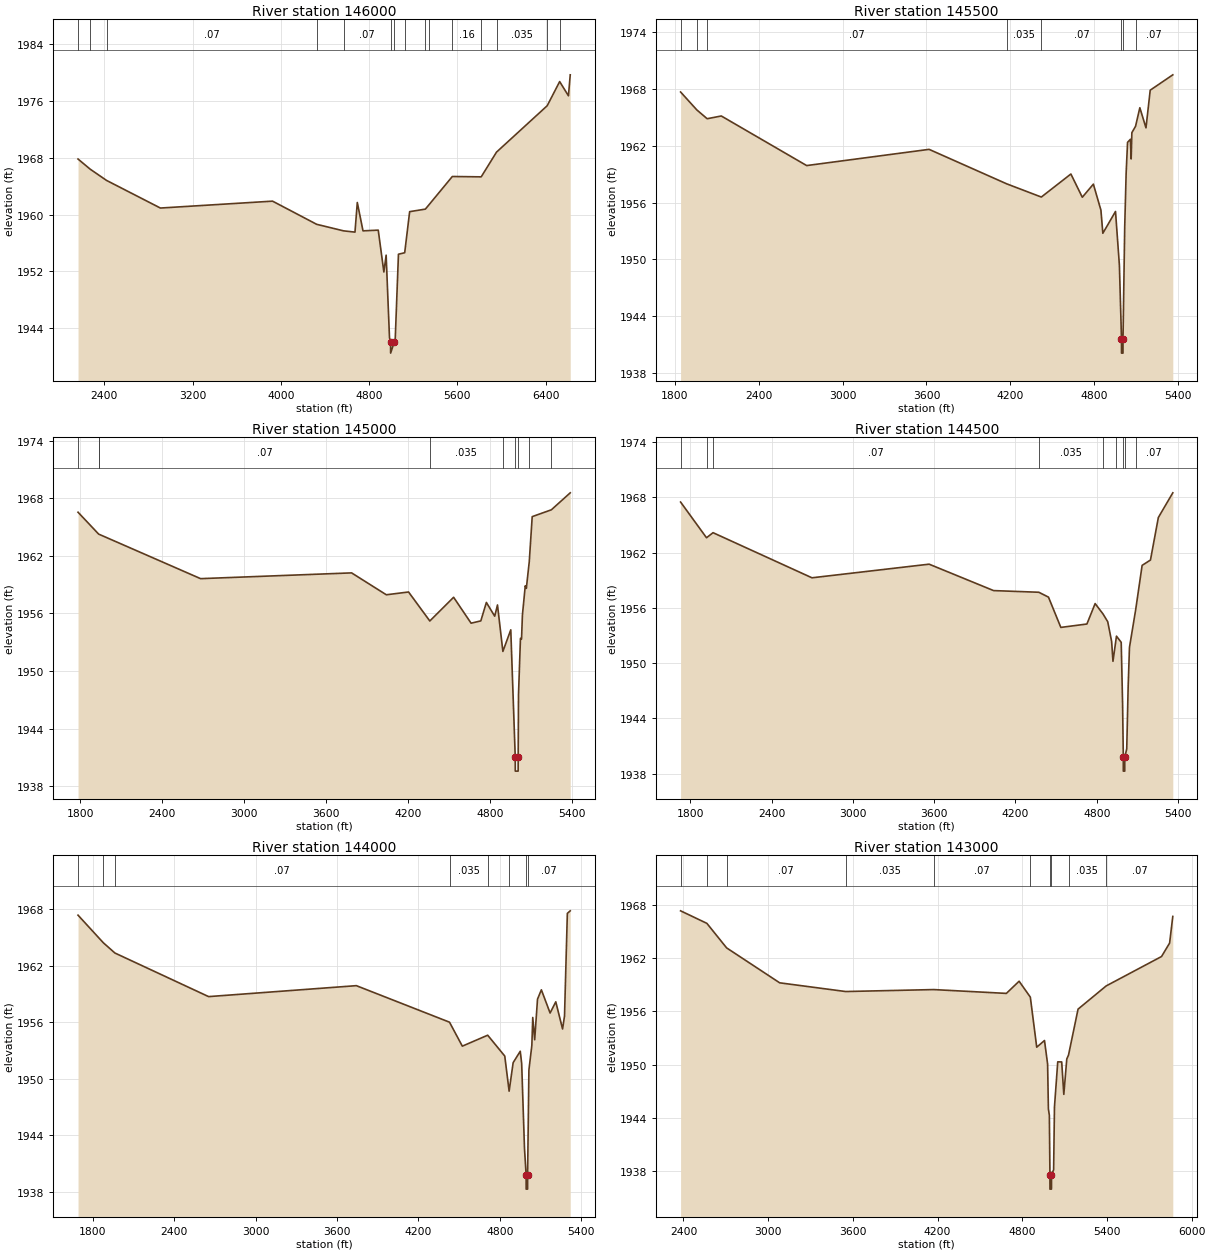
Type RM Length L Ch R = 1,146000,500,500,500
BEGIN DESCRIPTION:
Sweetwater Creek 291.0
END DESCRIPTION:
XS GIS Cut Line= 6
      1411867.10      6877949.73      1412104.76      6875887.48
      1411808.93      6875424.46      1411599.82      6875383.21
      1411372.04      6875343.16      1411204.90      6873961.70
#Sta/Elev= 30
  2161.5 1967.81  2271.8 1966.38  2419.9 1964.80  2908.1 1960.91  3924.8 1961.88
  4324.6 1958.62  4568.4 1957.70  4671.7 1957.52  4692.8 1961.69  4744.4 1957.70
  4882.6 1957.80  4933.6 1951.91  4954.2 1954.28  4984.5 1942.69  4994.5 1941.99
  4994.9 1940.49  5026.8 1941.99  5035.4 1941.99  5065.8 1954.41  5122.4 1954.62
  5167.3 1960.40  5309.8 1960.76  5338.2 1961.29  5554.1 1965.35  5815.8 1965.30
  5954.6 1968.78  6414.0 1975.31  6527.0 1978.71  6606.4 1976.71  6622.8 1979.66
#Mann=15,-1,0
  2161.5    0.07       0  2271.8   0.035       0  2419.9    0.07       0
  4324.6   0.035       0  4568.4    0.07       0  4994.5    0.07       0
  5026.8    0.07       0  5122.4    0.07       0  5309.8    0.16       0
  5338.2    0.07       0  5554.1    0.16       0  5815.8    0.07       0
  5954.6   0.035       0  6414.0   0.094       0  6527.0    0.07       0
Bank Sta=4994.5,5026.8
Exp/Cntr=0.3,0.1

Type RM Length L Ch R = 1,145500,500,500,500
BEGIN DESCRIPTION:
Sweetwater Creek 290.0
END DESCRIPTION:
XS GIS Cut Line= 5
      1411957.97      6877995.13      1411992.34      6877763.25
      1412248.60      6876034.29      1411700.06      6874995.03
      1411643.07      6874638.66
#Sta/Elev= 30
  1842.6 1967.66  1958.7 1965.77  2032.6 1964.84  2133.6 1965.13  2743.8 1959.90
  3618.9 1961.61  4174.2 1957.97  4421.1 1956.58  4632.5 1959.01  4714.0 1956.56
  4793.1 1957.94  4847.1 1955.20  4860.9 1952.76  4951.4 1955.06  4979.2 1949.39
  4994.2 1941.62  4994.3 1940.12  5004.8 1940.12  5005.0 1941.62  5017.2 1953.42
  5027.4 1959.10  5037.5 1962.35  5057.8 1962.67  5063.3 1960.60  5068.3 1963.37
  5094.6 1964.04  5125.3 1966.00  5169.2 1963.88  5199.5 1967.85  5360.9 1969.47
#Mann=8,-1,0
  1842.6    0.07       0  1958.7   0.035       0  2032.6    0.07       0
  4174.2   0.035       0  4421.1    0.07       0  4994.2    0.07       0
  5005.0    0.07       0  5094.6    0.07       0
Bank Sta=4994.2,5005
Exp/Cntr=0.3,0.1

Type RM Length L Ch R = 1,145000,500,500,500
BEGIN DESCRIPTION:
Sweetwater Creek 289.0
END DESCRIPTION:
XS GIS Cut Line= 4
      1412033.44      6878002.33      1412383.54      6876034.71
      1412151.42      6874837.64      1411848.82      6874591.12
#Sta/Elev= 30
  1782.1 1966.54  1933.4 1964.26  1935.0 1964.25  2680.6 1959.62  3787.5 1960.22
  4042.1 1957.94  4205.1 1958.23  4361.0 1955.21  4535.4 1957.68  4663.5 1954.98
  4734.8 1955.22  4775.5 1957.14  4836.7 1955.71  4857.0 1956.88  4896.6 1952.04
  4954.4 1954.29  4987.1 1941.07  4987.4 1939.57  5008.4 1939.57  5008.7 1941.07
  5011.0 1947.52  5025.4 1953.40  5033.3 1953.33  5039.8 1955.83  5060.6 1958.87
  5068.5 1958.61  5090.0 1961.40  5111.5 1966.08  5251.7 1966.79  5390.3 1968.56
#Mann=9,-1,0
  1782.1    0.07       0  1933.4   0.035       0  1935.0    0.07       0
  4361.0   0.035       0  4896.6    0.07       0  4987.1    0.07       0
  5008.7    0.07       0  5090.0    0.07       0  5251.7   0.035       0
Bank Sta=4987.1,5008.7
Exp/Cntr=0.3,0.1

Type RM Length L Ch R = 1,144500,500,500,500
BEGIN DESCRIPTION:
Sweetwater Creek 288.0
END DESCRIPTION:
XS GIS Cut Line= 4
      1412108.47      6878069.20      1412147.40      6877822.92
      1412619.14      6874838.41      1412705.00      6874487.98
#Sta/Elev= 30
  1729.1 1967.50  1920.4 1963.62  1968.6 1964.17  2698.4 1959.27  3562.8 1960.75
  4038.6 1957.88  4372.1 1957.70  4443.6 1957.17  4534.7 1953.88  4727.1 1954.25
  4787.8 1956.47  4846.5 1955.33  4880.7 1954.50  4909.3 1952.37  4919.4 1950.20
  4945.2 1952.93  4980.2 1952.26  4990.3 1945.62  4995.7 1939.77  4995.8 1938.27
  5006.3 1938.27  5006.5 1939.77  5021.0 1940.70  5031.3 1947.39  5041.1 1951.71
  5086.9 1955.80  5134.5 1960.62  5196.0 1961.20  5254.2 1965.82  5360.8 1968.50
#Mann=9,-1,0
  1729.1    0.07       0  1920.4   0.035       0  1968.6    0.07       0
  4372.1   0.035       0  4846.5    0.07       0  4945.2    0.16       0
  4995.7    0.07       0  5006.5    0.16       0  5086.9    0.07       0
Bank Sta=4995.7,5006.5
Exp/Cntr=0.3,0.1

Type RM Length L Ch R = 1,144000,1000,1000,1000
BEGIN DESCRIPTION:
Sweetwater Creek 286.0
END DESCRIPTION:
XS GIS Cut Line= 4
      1412140.66      6878077.62      1412190.86      6877905.45
      1413067.20      6874900.47      1413305.01      6874687.99
#Sta/Elev= 30
  1690.5 1967.34  1876.7 1964.42  1962.3 1963.33  2653.1 1958.71  3742.2 1959.87
  4428.9 1956.00  4523.4 1953.46  4710.4 1954.62  4836.3 1952.41  4868.4 1948.69
  4898.0 1951.71  4950.5 1952.92  4960.9 1951.62  4981.7 1942.62  4993.8 1939.81
  4994.0 1938.31  5004.5 1938.31  5004.6 1939.81  5014.2 1950.93  5035.9 1953.54
  5042.6 1956.50  5056.8 1954.14  5077.7 1958.44  5106.1 1959.43  5170.5 1956.97
  5212.3 1958.16  5262.4 1955.28  5276.7 1956.65  5297.6 1967.53  5318.9 1967.80
#Mann=8,-1,0
  1690.5    0.07       0  1876.7   0.035       0  1962.3    0.07       0
  4428.9   0.035       0  4710.4    0.07       0  4868.4    0.16       0
  4993.8    0.07       0  5004.6    0.07       0
Bank Sta=4993.8,5004.6
Exp/Cntr=0.3,0.1

Type RM Length L Ch R = 1,143000,500,500,500
BEGIN DESCRIPTION:
Sweetwater Creek 285.0
END DESCRIPTION:
XS GIS Cut Line= 4
      1412164.10      6878083.75      1412260.83      6877898.54
      1413377.36      6875760.92      1413855.02      6875037.97
#Sta/Elev= 30
  2379.4 1967.31  2565.7 1965.90  2705.6 1963.14  3081.5 1959.21  3548.9 1958.23
  4172.2 1958.45  4687.4 1958.02  4777.7 1959.39  4857.2 1957.60  4902.5 1951.97
  4957.5 1952.72  4979.6 1950.07  4985.2 1945.01  4992.0 1944.30  4996.1 1937.60
  4996.3 1936.00  5006.8 1936.00  5007.0 1937.60  5022.2 1938.18  5028.2 1945.25
  5051.4 1950.32  5079.4 1950.31  5094.4 1946.66  5115.5 1950.64  5127.8 1951.09
  5195.3 1956.25  5394.4 1958.86  5786.7 1962.17  5843.9 1963.68  5866.5 1966.68
#Mann=10,-1,0
  2379.4    0.07       0  2565.7   0.035       0  2705.6    0.07       0
  3548.9   0.035       0  4172.2    0.07       0  4857.2    0.16       0
  4996.1    0.07       0  5007.0    0.16       0  5127.8   0.035       0
  5394.4    0.07       0
Bank Sta=4996.1,5007
Exp/Cntr=0.3,0.1

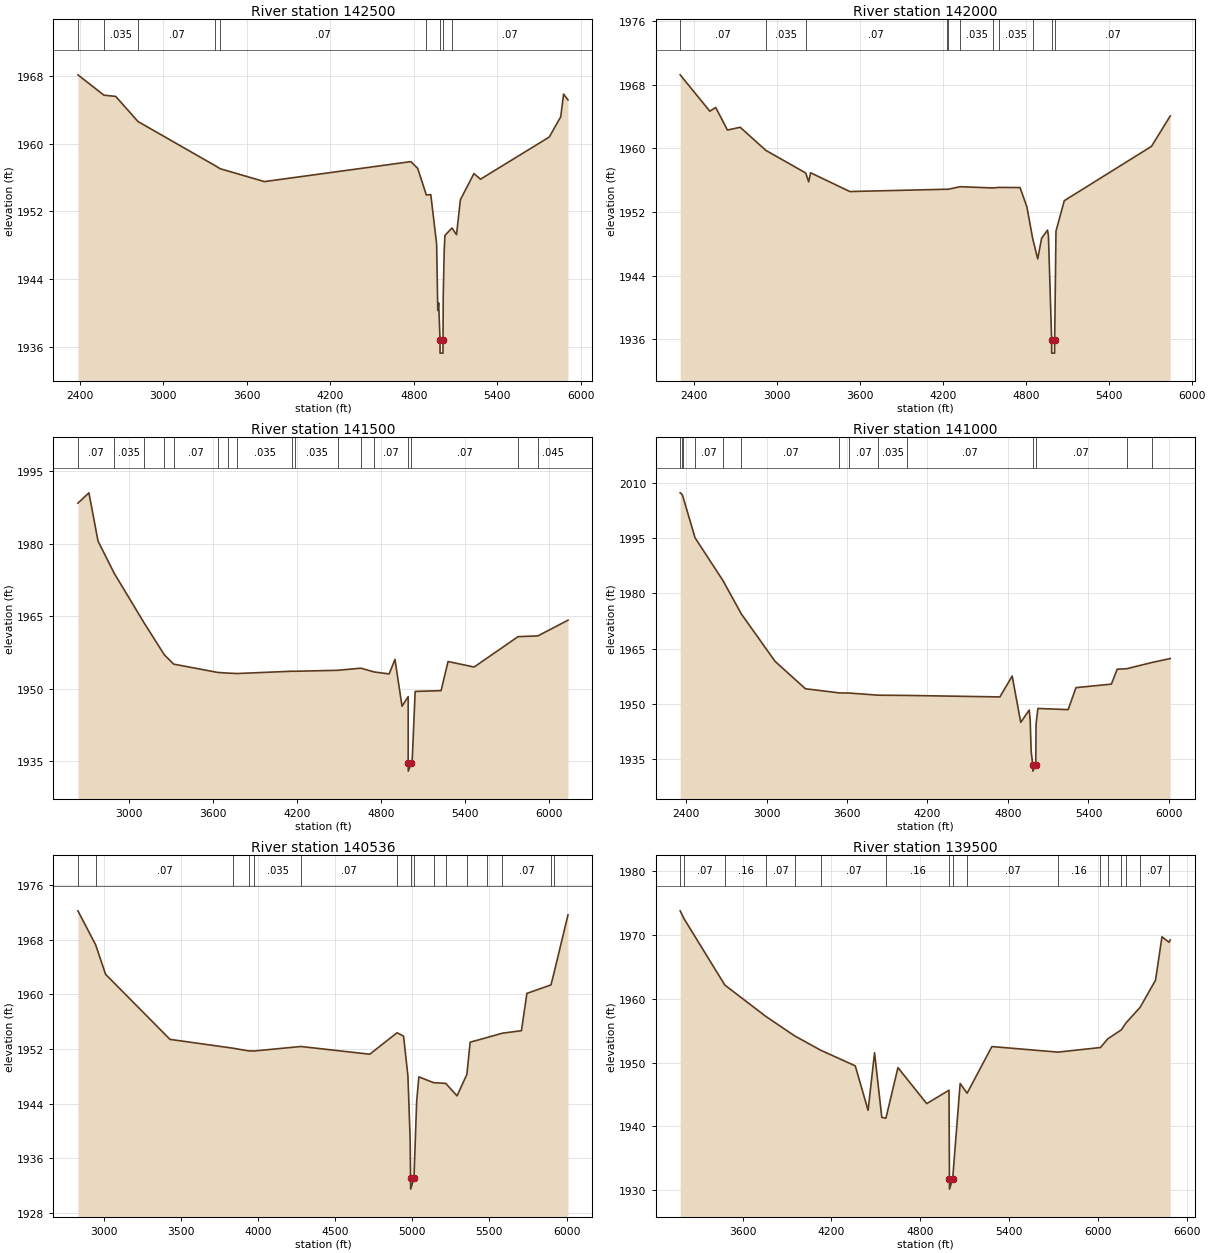
Type RM Length L Ch R = 1,142500,500,500,500
BEGIN DESCRIPTION:
Sweetwater Creek 284.0
END DESCRIPTION:
XS GIS Cut Line= 4
      1412241.25      6878103.98      1412330.55      6877980.81
      1413775.39      6875988.26      1413990.22      6875107.27
#Sta/Elev= 30
  2386.6 1968.14  2573.1 1965.74  2658.3 1965.59  2818.6 1962.62  3373.6 1957.40
  3408.6 1957.05  3726.0 1955.53  4778.0 1957.89  4827.4 1957.09  4889.4 1953.95
  4921.4 1953.99  4963.3 1948.16  4971.6 1940.31  4977.8 1941.19  4987.7 1936.87
  4988.0 1935.27  5009.0 1935.27  5009.3 1936.87  5010.6 1941.93  5017.6 1947.29
  5022.7 1949.17  5073.4 1950.05  5106.1 1949.26  5134.1 1953.39  5231.2 1956.48
  5278.2 1955.81  5772.2 1960.79  5854.6 1963.18  5875.2 1965.86  5906.8 1965.18
#Mann=9,-1,0
  2386.6    0.07       0  2573.1   0.035       0  2818.6    0.07       0
  3373.6   0.035       0  3408.6    0.07       0  4889.4    0.16       0
  4987.7    0.07       0  5009.3    0.16       0  5073.4    0.07       0
Bank Sta=4987.7,5009.3
Exp/Cntr=0.3,0.1

Type RM Length L Ch R = 1,142000,500,500,500
BEGIN DESCRIPTION:
Sweetwater Creek 283.0
END DESCRIPTION:
XS GIS Cut Line= 3
      1412402.99      6878099.05      1414234.15      6876116.94
      1414195.78      6875272.72
#Sta/Elev= 30
  2301.5 1969.23  2516.0 1964.66  2558.6 1965.12  2643.3 1962.29  2735.5 1962.64
  2920.6 1959.74  3209.7 1956.89  3230.5 1955.78  3244.7 1956.92  3528.2 1954.56
  4228.7 1954.85  4235.7 1954.83  4325.9 1955.17  4563.2 1955.01  4605.8 1955.08
  4759.2 1955.06  4808.5 1952.64  4851.0 1948.61  4886.8 1946.10  4915.1 1948.69
  4957.7 1949.71  4964.5 1948.98  4987.7 1935.85  4988.0 1934.25  5009.1 1934.25
  5009.4 1935.85  5019.0 1949.58  5079.0 1953.41  5709.7 1960.24  5845.1 1964.06
#Mann=11,-1,0
  2301.5    0.07       0  2920.6   0.035       0  3209.7    0.07       0
  4228.7   0.035       0  4235.7    0.07       0  4325.9   0.035       0
  4563.2    0.07       0  4605.8   0.035       0  4851.0    0.07       0
  4987.7    0.07       0  5009.4    0.07       0
Bank Sta=4987.7,5009.4
Exp/Cntr=0.3,0.1

Type RM Length L Ch R = 1,141500,500,500,500
BEGIN DESCRIPTION:
Sweetwater Creek 282.0
END DESCRIPTION:
XS GIS Cut Line= 4
      1413204.99      6878338.01      1414591.71      6876424.57
      1415005.46      6875890.05      1415285.42      6875528.39
#Sta/Elev= 30
  2636.9 1988.43  2715.4 1990.57  2780.4 1980.57  2896.1 1973.89  3107.0 1963.73
  3253.7 1957.00  3320.0 1955.08  3634.0 1953.36  3706.5 1953.22  3771.9 1953.13
  4166.4 1953.61  4187.9 1953.60  4491.8 1953.80  4654.9 1954.24  4751.7 1953.45
  4857.3 1953.05  4899.0 1956.06  4949.3 1946.36  4993.3 1948.35  4993.4 1934.51
  4993.7 1932.91  5015.0 1934.51  5021.0 1934.51  5043.1 1949.42  5227.8 1949.58
  5277.6 1955.62  5463.6 1954.48  5777.2 1960.77  5918.7 1960.93  6133.3 1964.18
#Mann=17,-1,0
  2636.9    0.07       0  2896.1   0.035       0  3107.0    0.07       0
  3253.7   0.035       0  3320.0    0.07       0  3634.0   0.035       0
  3706.5    0.07       0  3771.9   0.035       0  4166.4    0.07       0
  4187.9   0.035       0  4491.8    0.07       0  4654.9   0.035       0
  4751.7    0.07       0  4993.4    0.07       0  5015.0    0.07       0
  5777.2   0.035       0  5918.7   0.045       0
Bank Sta=4993.4,5015
Exp/Cntr=0.3,0.1

Type RM Length L Ch R = 1,141000,464,464,464
BEGIN DESCRIPTION:
Sweetwater Creek 281.0
END DESCRIPTION:
XS GIS Cut Line= 4
      1413155.01      6878537.99      1415003.32      6876647.78
      1415314.67      6876127.18      1415521.47      6875781.40
#Sta/Elev= 30
  2356.3 2007.33  2368.9 2006.96  2374.3 2006.61  2467.2 1995.12  2675.9 1983.45
  2812.0 1974.44  3063.4 1961.56  3289.8 1954.10  3543.4 1952.97  3615.3 1952.94
  3833.1 1952.35  4047.7 1952.29  4739.4 1951.88  4831.4 1957.55  4895.0 1944.97
  4958.5 1948.32  4965.7 1945.47  4972.7 1937.13  4985.1 1933.32  4985.4 1931.72
  5006.8 1933.32  5009.3 1944.52  5023.0 1948.75  5248.5 1948.43  5306.9 1954.40
  5570.7 1955.36  5614.2 1959.41  5685.0 1959.54  5873.7 1961.24  6009.5 1962.30
#Mann=14,-1,0
  2356.3   0.035       0  2368.9    0.07       0  2374.3   0.035       0
  2467.2    0.07       0  2675.9   0.035       0  2812.0    0.07       0
  3543.4   0.035       0  3615.3    0.07       0  3833.1   0.035       0
  4047.7    0.07       0  4985.1    0.07       0  5006.8    0.07       0
  5685.0   0.035       0  5873.7    0.07       0
Bank Sta=4985.1,5006.8
Exp/Cntr=0.3,0.1

Type RM Length L Ch R = 1,140536,1036,1036,1036
BEGIN DESCRIPTION:
Sweetwater Creek 280.0
END DESCRIPTION:
XS GIS Cut Line= 3
      1413697.50      6878492.08      1413759.82      6878404.66
      1415967.53      6876274.19
#Sta/Elev= 30
  2833.6 1972.20  2948.5 1967.23  3013.0 1962.92  3430.3 1953.41  3838.4 1952.12
  3939.0 1951.73  3975.5 1951.71  4278.1 1952.37  4724.5 1951.24  4901.6 1954.38
  4943.7 1953.88  4972.0 1948.04  4986.2 1938.93  4989.2 1933.12  4989.5 1931.52
  5010.9 1933.12  5028.6 1944.35  5042.8 1947.93  5138.3 1947.08  5216.9 1946.98
  5290.2 1945.15  5353.9 1948.30  5375.1 1953.00  5483.3 1953.67  5582.7 1954.31
  5707.5 1954.68  5742.7 1960.13  5898.7 1961.37  5919.9 1963.25  6009.0 1971.61
#Mann=16,-1,0
  2833.6   0.035       0  2948.5    0.07       0  3838.4   0.035       0
  3939.0    0.07       0  3975.5   0.035       0  4278.1    0.07       0
  4901.6    0.16       0  4989.2    0.07       0  5010.9    0.16       0
  5138.3    0.07       0  5216.9    0.16       0  5353.9    0.07       0
  5483.3   0.035       0  5582.7    0.07       0  5898.7   0.035       0
  5919.9    0.07       0
Bank Sta=4989.2,5010.9
Exp/Cntr=0.3,0.1

Type RM Length L Ch R = 1,139500,1000,1000,1000
BEGIN DESCRIPTION:
Sweetwater Creek 278.0
END DESCRIPTION:
XS GIS Cut Line= 5
      1413732.35      6878647.69      1414526.34      6878412.45
      1415344.16      6877848.53      1415455.00      6877788.00
      1416283.79      6876708.57
#Sta/Elev= 30
  3178.5 1973.78  3205.6 1972.51  3480.0 1962.15  3758.4 1957.21  3952.6 1954.17
  4129.8 1951.91  4360.6 1949.49  4447.2 1942.52  4490.9 1951.54  4539.8 1941.41
  4567.5 1941.28  4648.8 1949.21  4843.1 1943.57  4993.5 1945.67  4996.5 1931.77
  4996.8 1930.17  5018.1 1931.77  5068.9 1946.72  5115.8 1945.20  5283.1 1952.51
  5728.8 1951.64  6016.1 1952.36  6065.6 1953.72  6158.0 1955.15  6186.5 1956.16
  6284.2 1958.67  6387.9 1962.91  6431.4 1969.71  6479.4 1968.85  6487.2 1969.22
#Mann=17,-1,0
  3178.5   0.035       0  3205.6    0.07       0  3480.0    0.16       0
  3758.4    0.07       0  3952.6    0.16       0  4129.8    0.07       0
  4567.5    0.16       0  4996.5    0.07       0  5018.1    0.16       0
  5115.8    0.07       0  5728.8    0.16       0  6016.1    0.07       0
  6065.6    0.16       0  6158.0    0.07       0  6186.5   0.035       0
  6284.2    0.07       0  6479.4   0.035       0
Bank Sta=4996.5,5018.1
Exp/Cntr=0.3,0.1

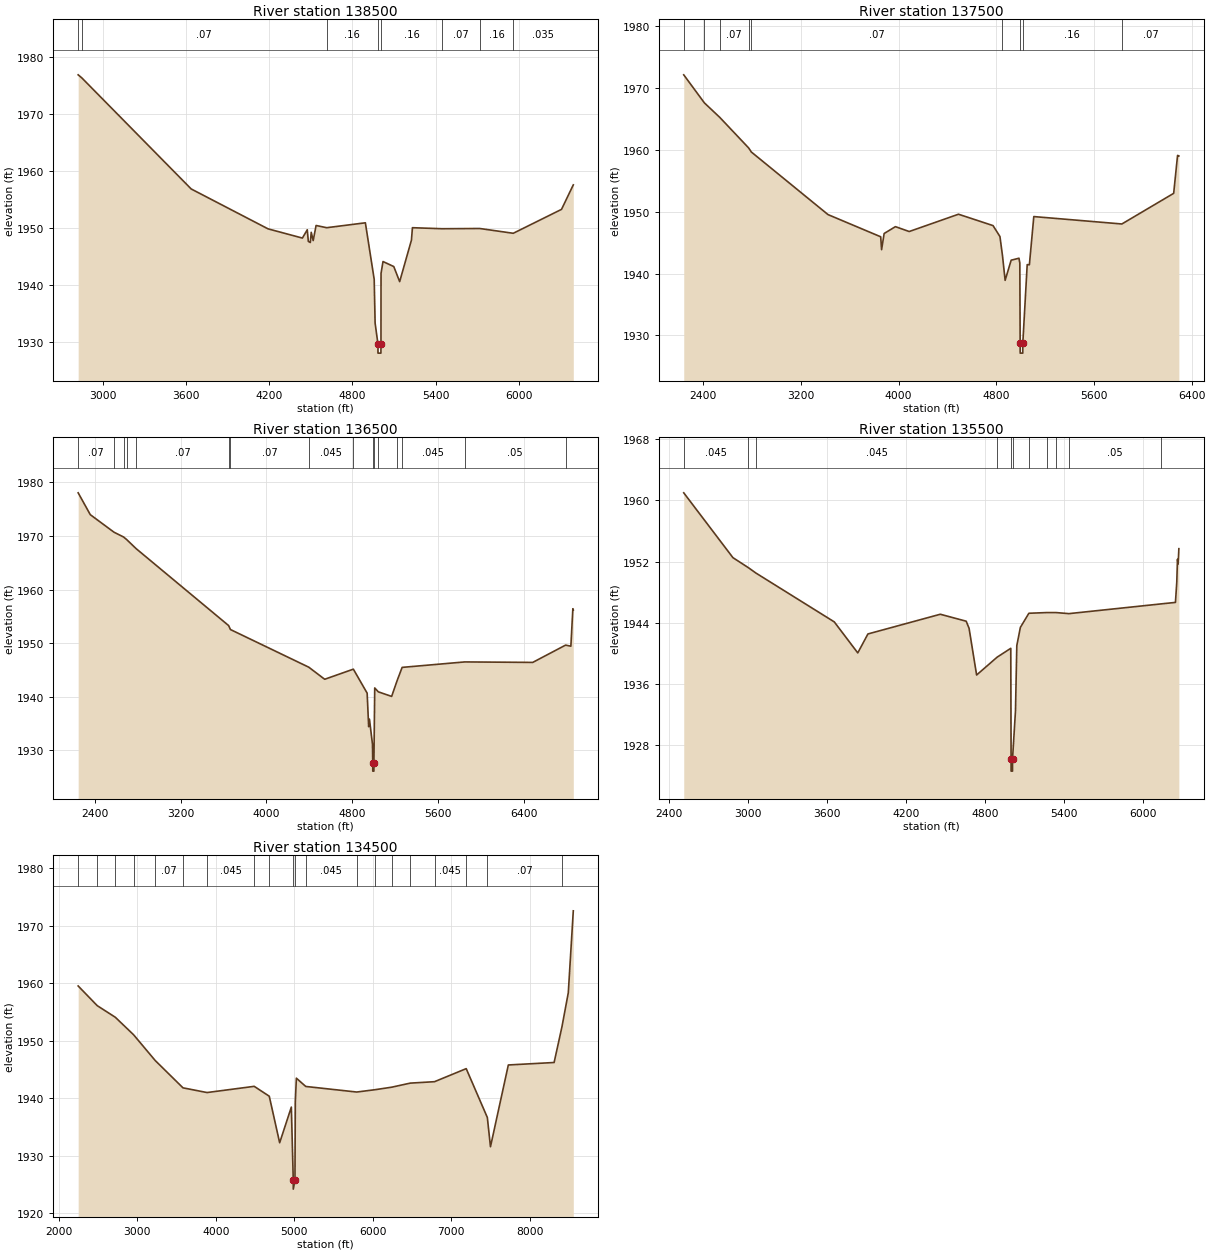
Type RM Length L Ch R = 1,138500,1000,1000,1000
BEGIN DESCRIPTION:
Sweetwater Creek 276.0
END DESCRIPTION:
XS GIS Cut Line= 3
      1414039.82      6879812.95      1415684.65      6878387.73
      1416654.99      6877388.01
#Sta/Elev= 30
  2823.6 1976.95  2849.6 1976.42  3638.5 1956.91  4192.3 1949.91  4440.2 1948.29
  4475.3 1949.75  4482.9 1947.71  4497.2 1947.51  4503.8 1949.30  4518.0 1947.85
  4538.9 1950.50  4615.4 1950.11  4894.2 1950.97  4957.8 1941.05  4964.4 1933.37
  4984.9 1929.69  4985.2 1928.09  5006.3 1928.09  5006.6 1929.69  5007.1 1942.08
  5021.3 1944.17  5099.0 1943.29  5141.4 1940.64  5226.3 1947.93  5233.5 1950.11
  5447.4 1949.93  5718.9 1949.97  5960.3 1949.13  6308.4 1953.33  6393.2 1957.63
#Mann=8,-1,0
  2823.6    0.16       0  2849.6    0.07       0  4615.4    0.16       0
  4984.9    0.07       0  5006.6    0.16       0  5447.4    0.07       0
  5718.9    0.16       0  5960.3   0.035       0
Bank Sta=4984.9,5006.6
Exp/Cntr=0.3,0.1

Type RM Length L Ch R = 1,137500,1000,1000,1000
BEGIN DESCRIPTION:
Sweetwater Creek 274.0
END DESCRIPTION:
XS GIS Cut Line= 3
      1414605.03      6880437.97      1416625.42      6878558.23
      1417060.27      6877338.00
#Sta/Elev= 30
  2240.4 1972.17  2409.5 1967.63  2534.7 1965.30  2772.8 1960.32  2794.0 1959.68
  3422.0 1949.55  3853.4 1945.96  3860.7 1943.87  3881.7 1946.49  3974.1 1947.60
  4087.0 1946.81  4490.5 1949.61  4773.4 1947.77  4830.1 1946.00  4850.9 1942.91
  4872.6 1938.91  4921.9 1942.17  4985.8 1942.49  4992.8 1941.72  4995.6 1928.73
  4995.9 1927.13  5017.0 1927.13  5017.3 1928.73  5053.3 1941.45  5071.2 1941.43
  5107.4 1949.23  5828.6 1948.03  6252.9 1952.99  6284.8 1959.13  6295.4 1959.04
#Mann=9,-1,0
  2240.4    0.07       0  2409.5    0.16       0  2534.7    0.07       0
  2772.8    0.16       0  2794.0    0.07       0  4850.9    0.16       0
  4995.6    0.07       0  5017.3    0.16       0  5828.6    0.07       0
Bank Sta=4995.6,5017.3
Exp/Cntr=0.3,0.1

Type RM Length L Ch R = 1,136500,1000,1000,1000
BEGIN DESCRIPTION:
Sweetwater Creek 272.0
END DESCRIPTION:
XS GIS Cut Line= 3
      1415054.99      6881238.01      1417050.15      6879338.47
      1417380.14      6877505.74
#Sta/Elev= 30
  2245.2 1978.06  2358.3 1973.98  2579.6 1970.70  2668.3 1969.81  2696.3 1969.35
  2785.3 1967.64  3648.3 1953.26  3665.3 1952.52  4395.2 1945.49  4544.0 1943.23
  4811.4 1945.12  4940.0 1940.63  4954.1 1934.37  4961.4 1935.78  4989.7 1931.08
  4992.1 1927.67  4992.3 1926.07  5002.8 1926.07  5003.0 1927.67  5010.6 1941.61
  5044.2 1940.88  5168.3 1940.03  5219.6 1942.99  5266.2 1945.45  5849.5 1946.47
  6484.0 1946.38  6790.2 1949.61  6839.6 1949.41  6858.1 1956.41  6862.2 1956.18
#Mann=16,-1,0
  2245.2    0.07       0  2579.6    0.16       0  2668.3    0.07       0
  2696.3    0.16       0  2785.3    0.07       0  3648.3    0.16       0
  3665.3    0.07       0  4395.2   0.045       0  4811.4    0.07       0
  4992.1    0.07       0  5003.0    0.07       0  5044.2   0.045       0
  5219.6    0.07       0  5266.2   0.045       0  5849.5    0.05       0
  6790.2    0.07       0
Bank Sta=4992.1,5003
Exp/Cntr=0.3,0.1

Type RM Length L Ch R = 1,135500,1000,1000,1000
BEGIN DESCRIPTION:
Sweetwater Creek 270.0
END DESCRIPTION:
XS GIS Cut Line= 4
      1416541.17      6880947.67      1417792.58      6879319.47
      1417860.96      6878887.50      1417658.34      6877632.35
#Sta/Elev= 30
  2509.1 1960.99  2882.7 1952.51  2998.9 1951.21  3057.7 1950.49  3653.0 1944.10
  3831.5 1940.04  3908.7 1942.52  4458.6 1945.10  4655.3 1944.19  4677.3 1943.26
  4734.6 1937.15  4890.2 1939.48  4994.1 1940.64  4996.6 1926.17  4996.7 1924.57
  5007.3 1924.57  5007.4 1926.17  5029.9 1932.45  5040.0 1941.00  5067.1 1943.38
  5131.7 1945.23  5268.7 1945.32  5337.5 1945.32  5435.7 1945.18  6134.1 1946.45
  6245.4 1946.65  6255.5 1949.28  6260.8 1952.29  6265.9 1951.67  6271.4 1953.68
#Mann=11,-1,0
  2509.1   0.045       0  2998.9    0.07       0  3057.7   0.045       0
  4890.2    0.07       0  4996.6    0.07       0  5007.4    0.07       0
  5131.7   0.045       0  5268.7    0.05       0  5337.5   0.045       0
  5435.7    0.05       0  6134.1    0.07       0
Bank Sta=4996.6,5007.4
Exp/Cntr=0.3,0.1

Type RM Length L Ch R = 1,134500,1000,1000,1000
BEGIN DESCRIPTION:
Sweetwater Creek 268.0
END DESCRIPTION:
XS GIS Cut Line= 4
      1416755.04      6881087.97      1418749.86      6879190.39
      1418968.66      6878863.57      1421681.25      6877238.36
#Sta/Elev= 30
  2246.8 1959.51  2489.2 1956.09  2719.5 1954.07  2952.1 1951.03  3228.2 1946.54
  3582.3 1941.78  3888.8 1940.96  4489.7 1942.04  4681.7 1940.32  4814.2 1932.22
  4963.0 1938.43  4987.4 1925.75  4987.7 1924.15  5009.1 1925.75  5013.6 1939.29
  5026.9 1943.46  5146.7 1942.02  5796.0 1941.05  6032.2 1941.46  6241.2 1941.89
  6477.4 1942.60  6787.0 1942.85  7191.1 1945.12  7460.3 1936.62  7500.3 1931.53
  7727.8 1945.76  8311.1 1946.19  8411.2 1952.42  8491.9 1958.34  8555.5 1972.59
#Mann=20,-1,0
  2246.8   0.045       0  2489.2   0.045       0  2719.5    0.07       0
  2952.1   0.045       0  3228.2    0.07       0  3582.3   0.045       0
  3888.8   0.045       0  4489.7    0.07       0  4681.7    0.16       0
  4987.4    0.07       0  5009.1    0.16       0  5146.7   0.045       0
  5796.0    0.07       0  6032.2   0.035       0  6241.2    0.07       0
  6477.4   0.035       0  6787.0   0.045       0  7191.1   0.035       0
  7460.3    0.07       0  8411.2    0.16       0
Bank Sta=4987.4,5009.1
Exp/Cntr=0.3,0.1