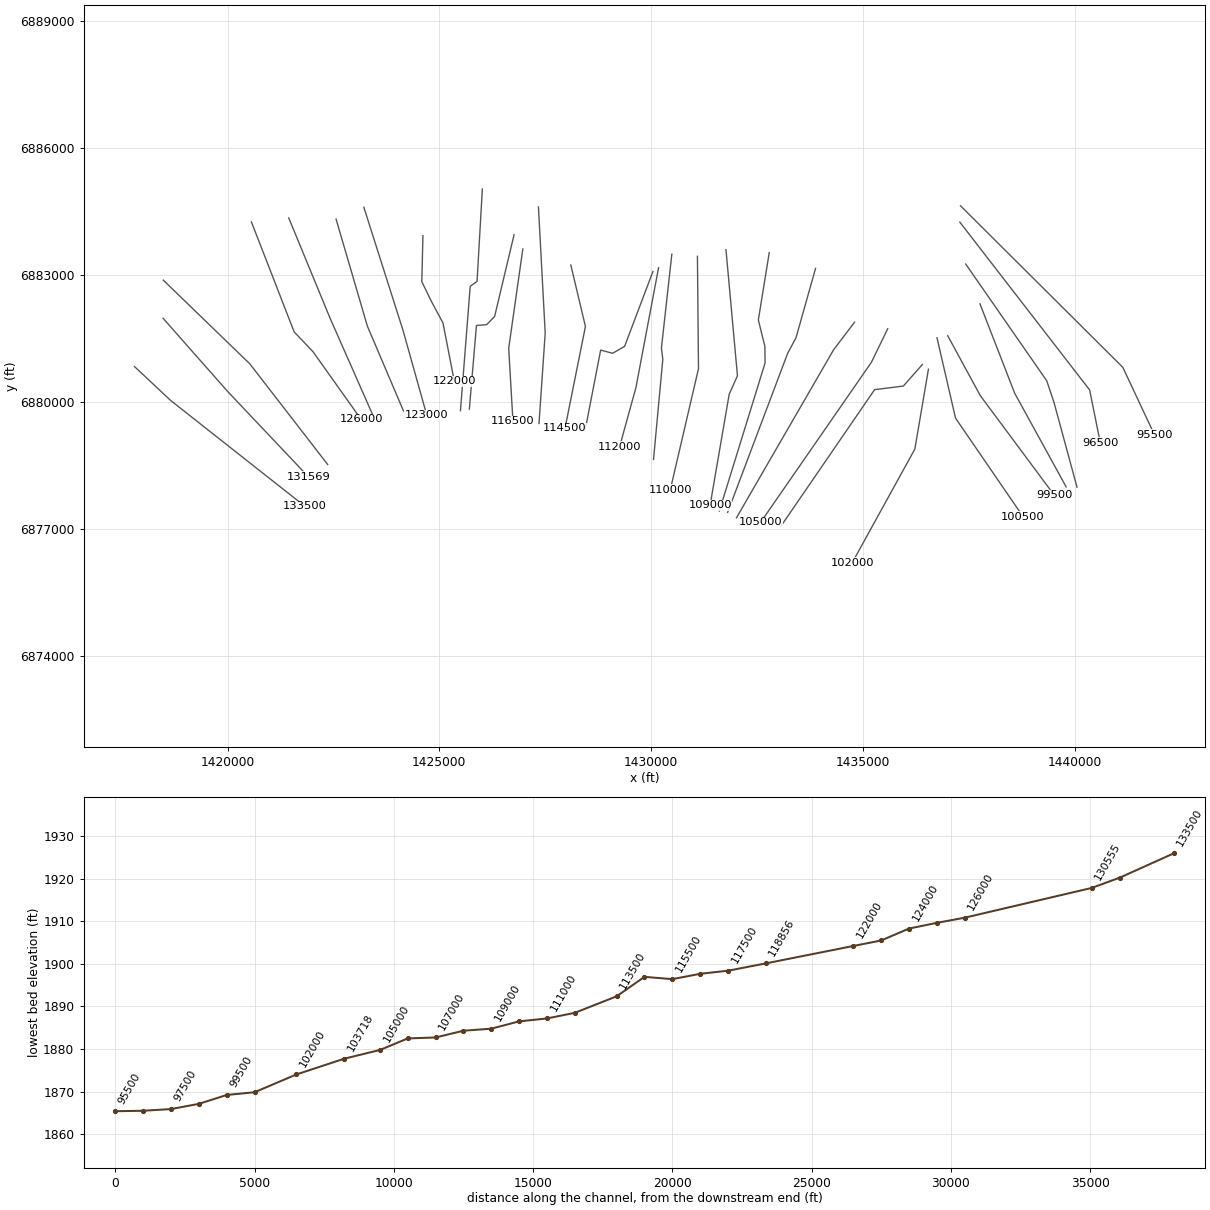
HEC-RAS study Sweetwater Creek.prj: Sweetwater Creek Base Level Engineering

--- Sweetwater Creek.g01 (geometry) --- (continued)

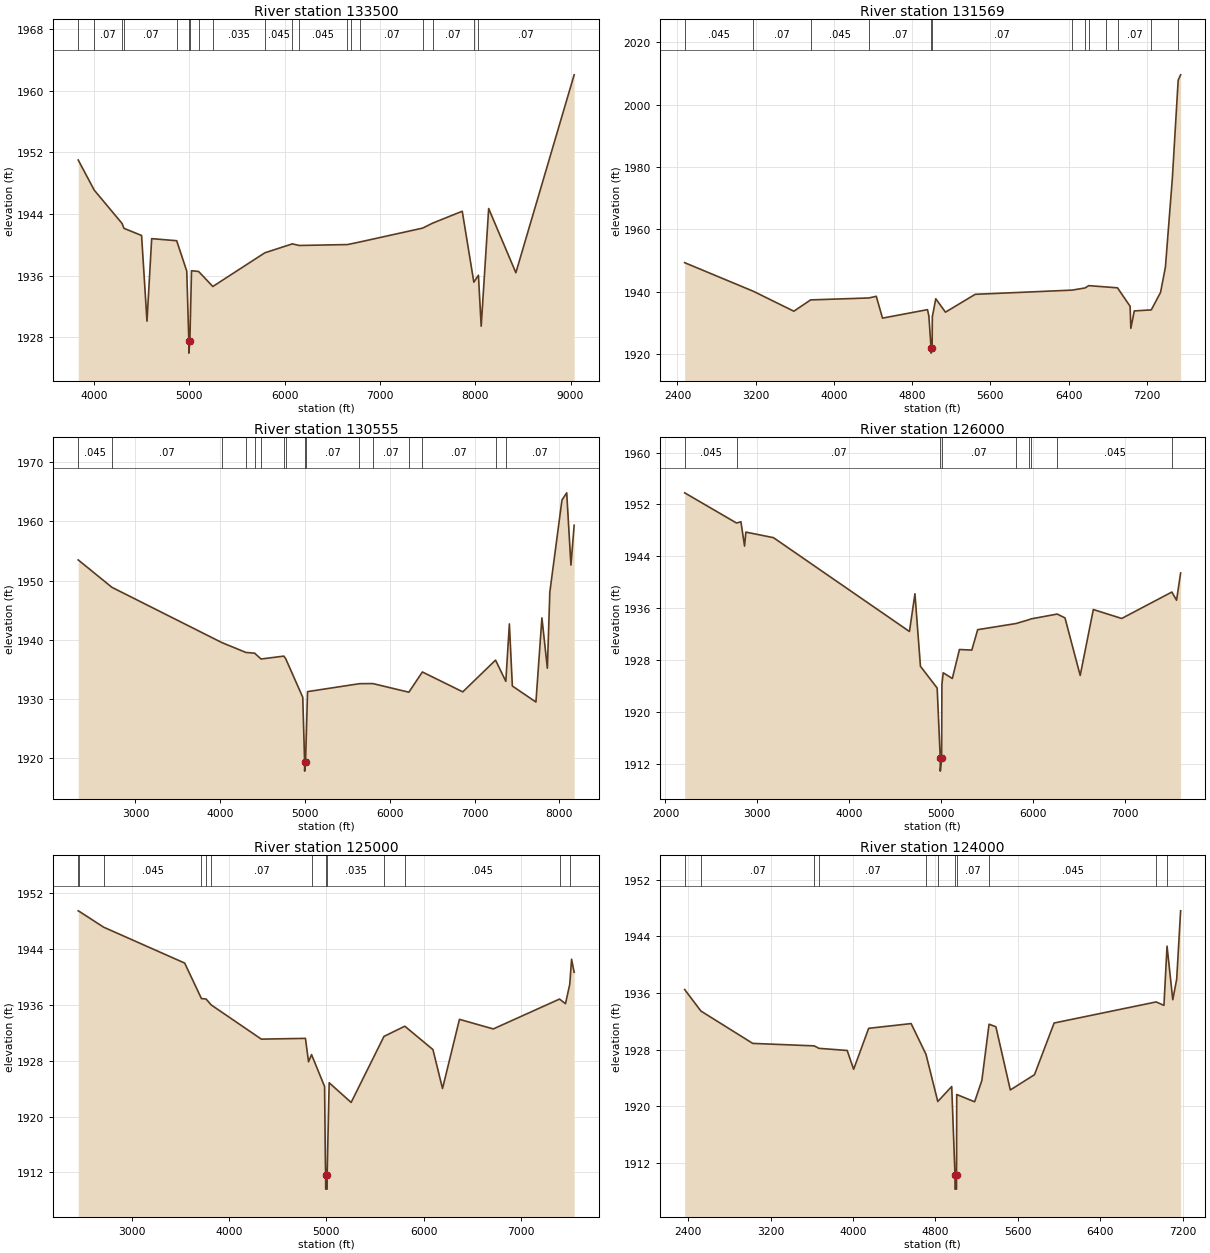
Type RM Length L Ch R = 1,133500,1931,1931,1931
BEGIN DESCRIPTION:
Sweetwater Creek 265.0
END DESCRIPTION:
XS GIS Cut Line= 3
      1417804.98      6880838.01      1418654.98      6880039.13
      1421825.15      6877538.20
#Sta/Elev= 30
  3833.5 1951.02  4001.9 1947.10  4293.9 1942.77  4313.5 1942.14  4498.5 1941.21
  4555.2 1930.07  4604.5 1940.80  4866.9 1940.53  4972.6 1936.58  4994.3 1927.52
  4994.4 1925.92  5005.1 1927.52  5022.6 1936.63  5097.1 1936.53  5246.2 1934.58
  5791.9 1938.96  6080.6 1940.12  6153.9 1939.91  6658.8 1940.03  6695.1 1940.12
  6790.6 1940.37  7448.3 1942.17  7552.2 1942.81  7863.6 1944.36  7985.3 1935.14
  8033.4 1936.04  8062.4 1929.42  8140.9 1944.71  8426.3 1936.37  9037.9 1962.09
#Mann=19,-1,0
  3833.5   0.045       0  4001.9    0.07       0  4293.9   0.045       0
  4313.5    0.07       0  4866.9    0.16       0  4994.3    0.07       0
  5005.1    0.16       0  5097.1    0.07       0  5246.2   0.035       0
  5791.9   0.045       0  6080.6    0.07       0  6153.9   0.045       0
  6658.8    0.07       0  6695.1   0.045       0  6790.6    0.07       0
  7448.3   0.035       0  7552.2    0.07       0  7985.3   0.035       0
  8033.4    0.07       0
Bank Sta=4994.3,5005.1
Exp/Cntr=0.3,0.1

Type RM Length L Ch R = 1,131569,1014,1014,1014
BEGIN DESCRIPTION:
Sweetwater Creek 261.0
END DESCRIPTION:
XS GIS Cut Line= 3
      1418479.56      6881978.11      1420000.72      6880252.95
      1421904.97      6878238.03
#Sta/Elev= 30
  2473.9 1949.28  3176.8 1940.09  3590.4 1933.70  3762.3 1937.33  4357.7 1937.95
  4433.7 1938.48  4497.3 1931.48  4957.4 1934.20  4971.6 1932.16  4993.8 1921.84
  4994.0 1920.24  5004.7 1921.84  5006.8 1931.91  5042.2 1937.70  5141.1 1933.39
  5445.3 1939.12  6436.8 1940.47  6568.1 1941.16  6607.3 1941.91  6785.5 1941.48
  6900.8 1941.21  7029.9 1935.27  7037.2 1928.21  7072.4 1933.79  7246.3 1934.12
  7341.0 1939.73  7390.8 1947.85  7461.6 1976.32  7521.4 2007.88  7546.3 2009.59
#Mann=13,-1,0
  2473.9   0.045       0  3176.8    0.07       0  3762.3   0.045       0
  4357.7    0.07       0  4993.8    0.07       0  5004.7    0.07       0
  6436.8   0.035       0  6568.1   0.063       0  6607.3    0.07       0
  6785.5   0.035       0  6900.8    0.07       0  7246.3    0.16       0
  7521.4    0.07       0
Bank Sta=4993.8,5004.7
Exp/Cntr=0.3,0.1

Type RM Length L Ch R = 1,130555,4555,4555,4555
BEGIN DESCRIPTION:
Sweetwater Creek 257.0
END DESCRIPTION:
XS GIS Cut Line= 3
      1418483.06      6882881.22      1420525.16      6880904.22
      1422364.44      6878524.71
#Sta/Elev= 30
  2324.8 1953.49  2722.4 1948.86  4019.7 1939.52  4302.7 1937.86  4406.3 1937.73
  4481.3 1936.75  4750.3 1937.24  4771.7 1936.82  4973.3 1930.29  4995.4 1919.41
  4995.6 1917.81  5006.3 1919.41  5029.9 1931.24  5641.7 1932.58  5799.6 1932.60
  6225.1 1931.14  6384.4 1934.56  6860.8 1931.20  7247.4 1936.56  7368.6 1932.98
  7410.5 1942.68  7445.8 1932.19  7723.8 1929.48  7794.4 1943.70  7858.7 1935.20
  7887.7 1948.05  8030.8 1963.60  8086.9 1964.82  8136.7 1952.62  8174.6 1959.34
#Mann=16,-1,0
  2324.8   0.045       0  2722.4    0.07       0  4019.7    0.16       0
  4302.7    0.07       0  4406.3    0.16       0  4481.3    0.07       0
  4750.3   0.045       0  4771.7    0.07       0  4995.4    0.07       0
  5006.3    0.07       0  5641.7   0.045       0  5799.6    0.07       0
  6225.1   0.045       0  6384.4    0.07       0  7247.4   0.035       0
  7368.6    0.07       0
Bank Sta=4995.4,5006.3
Exp/Cntr=0.3,0.1

Type RM Length L Ch R = 1,126000,1000,1000,1000
BEGIN DESCRIPTION:
Sweetwater Creek 251.0
END DESCRIPTION:
XS GIS Cut Line= 4
      1420563.61      6884258.42      1421573.71      6881656.84
      1422015.85      6881192.92      1423152.44      6879592.52
#Sta/Elev= 30
  2209.2 1953.78  2773.1 1949.12  2821.1 1949.32  2860.5 1945.56  2874.7 1947.72
  3175.1 1946.86  4654.2 1932.38  4714.0 1938.20  4773.8 1927.01  4955.8 1923.65
  4989.3 1912.83  4989.5 1910.83  5004.1 1912.83  5007.2 1924.20  5021.4 1926.01
  5120.4 1925.13  5198.1 1929.60  5332.4 1929.51  5396.3 1932.66  5813.5 1933.61
  5958.7 1934.22  5972.1 1934.31  6261.1 1935.07  6346.0 1934.48  6511.6 1925.60
  6654.2 1935.77  6963.0 1934.39  7508.9 1938.47  7559.6 1937.20  7603.8 1941.41
#Mann=9,-1,0
  2209.2   0.045       0  2773.1    0.07       0  4989.3    0.07       0
  5004.1    0.07       0  5813.5   0.035       0  5958.7    0.07       0
  5972.1   0.035       0  6261.1   0.045       0  7508.9   0.035       0
Bank Sta=4989.3,5004.1
Exp/Cntr=0.3,0.1

Type RM Length L Ch R = 1,125000,1000,1000,1000
BEGIN DESCRIPTION:
Sweetwater Creek 249.0
END DESCRIPTION:
XS GIS Cut Line= 3
      1421445.19      6884351.77      1422418.31      6881988.04
      1423446.97      6879653.64
#Sta/Elev= 30
  2443.8 1949.42  2456.7 1949.32  2705.9 1947.08  3540.1 1941.95  3713.0 1936.87
  3760.4 1936.81  3813.7 1935.96  4329.6 1931.07  4783.8 1931.18  4815.7 1927.83
  4846.6 1928.86  4981.0 1924.30  4989.2 1913.41  4992.3 1911.62  4992.5 1909.62
  5007.0 1909.62  5007.1 1911.62  5028.2 1924.83  5254.5 1922.02  5592.6 1931.46
  5807.1 1932.92  6096.8 1929.58  6195.6 1924.01  6369.8 1933.90  6718.3 1932.53
  7400.2 1936.80  7461.8 1936.14  7505.9 1938.92  7524.4 1942.50  7551.0 1940.63
#Mann=13,-1,0
  2443.8   0.045       0  2456.7    0.07       0  2705.9   0.045       0
  3713.0    0.07       0  3760.4   0.045       0  3813.7    0.07       0
  4846.6   0.035       0  4992.3    0.07       0  5007.1   0.035       0
  5592.6   0.035       0  5807.1   0.045       0  7400.2   0.035       0
  7505.9    0.07       0
Bank Sta=4992.3,5007.1
Exp/Cntr=0.3,0.1

Type RM Length L Ch R = 1,124000,1000,1000,1000
BEGIN DESCRIPTION:
Sweetwater Creek 247.0
END DESCRIPTION:
XS GIS Cut Line= 3
      1422563.05      6884322.05      1423302.08      6881794.26
      1424154.98      6879788.04
#Sta/Elev= 30
  2366.4 1936.48  2524.1 1933.44  3027.0 1928.87  3624.1 1928.52  3669.8 1928.17
  3943.8 1927.87  4006.3 1925.21  4152.2 1931.00  4564.3 1931.67  4708.6 1927.33
  4823.0 1920.66  4958.3 1922.78  4990.1 1910.28  4990.3 1908.28  5004.8 1908.28
  5004.9 1910.28  5006.8 1921.65  5180.7 1920.62  5250.8 1923.63  5320.7 1931.58
  5387.1 1931.22  5527.2 1922.29  5761.7 1924.45  5952.2 1931.75  6943.0 1934.73
  7018.2 1934.24  7048.2 1942.61  7104.0 1935.04  7141.9 1937.95  7180.0 1947.60
#Mann=11,-1,0
  2366.4   0.035       0  2524.1    0.07       0  3624.1    0.16       0
  3669.8    0.07       0  4708.6   0.035       0  4823.0    0.07       0
  4990.1    0.07       0  5004.9    0.07       0  5320.7   0.045       0
  6943.0   0.035       0  7048.2    0.07       0
Bank Sta=4990.1,5004.9
Exp/Cntr=0.3,0.1

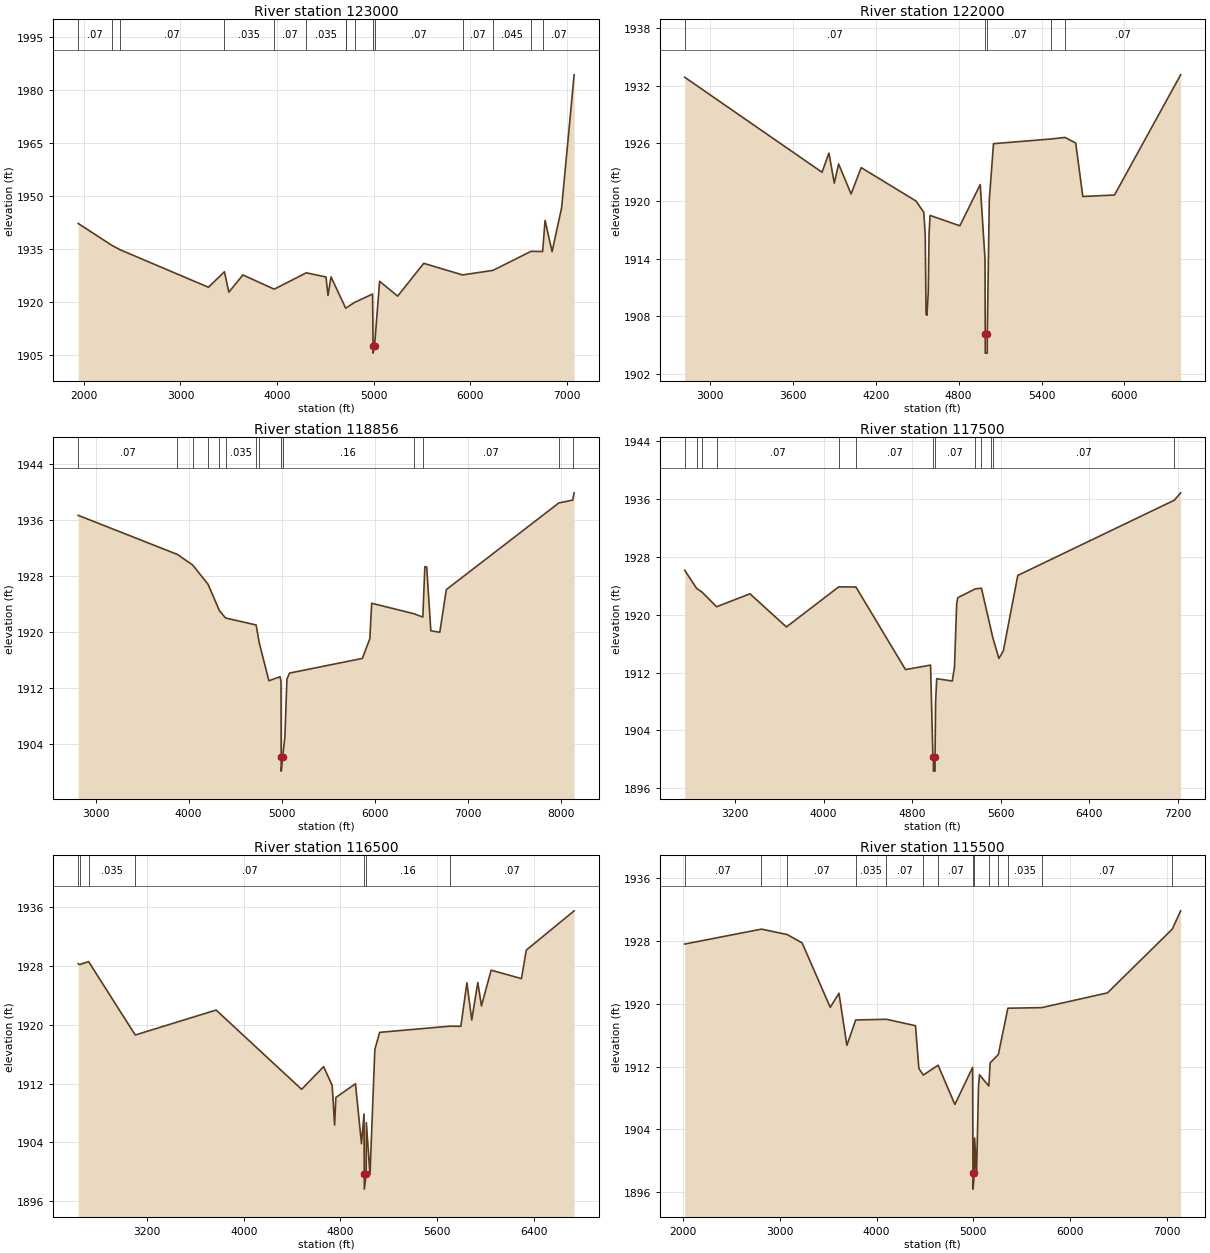
Type RM Length L Ch R = 1,123000,1000,1000,1000
BEGIN DESCRIPTION:
Sweetwater Creek 245.0
END DESCRIPTION:
XS GIS Cut Line= 3
      1423218.63      6884603.21      1424145.21      6881688.02
      1424705.00      6879687.99
#Sta/Elev= 30
  1941.1 1942.21  2287.9 1936.04  2371.5 1934.80  3289.7 1924.14  3455.4 1928.53
  3501.0 1922.75  3646.4 1927.63  3970.8 1923.59  4302.9 1928.23  4506.9 1927.05
  4527.8 1921.82  4559.3 1927.07  4710.3 1918.25  4716.0 1918.29  4802.6 1919.84
  4989.5 1922.22  4994.8 1907.48  4994.9 1905.48  5009.6 1907.48  5062.3 1925.82
  5249.2 1921.63  5519.2 1930.91  5921.5 1927.63  6237.0 1928.93  6629.9 1934.31
  6750.6 1934.26  6775.7 1943.06  6848.4 1934.22  6947.1 1946.66  7076.9 1984.31
#Mann=15,-1,0
  1941.1    0.07       0  2287.9   0.035       0  2371.5    0.07       0
  3455.4   0.035       0  3970.8    0.07       0  4302.9   0.035       0
  4710.3    0.07       0  4716.0   0.035       0  4802.6    0.07       0
  4994.8    0.07       0  5009.6    0.07       0  5921.5    0.07       0
  6237.0   0.045       0  6629.9   0.035       0  6750.6    0.07       0
Bank Sta=4994.8,5009.6
Exp/Cntr=0.3,0.1

Type RM Length L Ch R = 1,122000,3144,3144,3144
BEGIN DESCRIPTION:
Sweetwater Creek 241.0
END DESCRIPTION:
XS GIS Cut Line= 5
      1424613.88      6883932.30      1424586.82      6882845.32
      1424812.97      6882379.48      1425086.75      6881869.35
      1425355.01      6880487.96
#Sta/Elev= 30
  2815.9 1932.88  3810.5 1923.00  3860.5 1924.99  3899.4 1921.87  3930.7 1923.86
  4021.0 1920.74  4094.2 1923.48  4490.8 1920.01  4547.6 1918.83  4558.0 1916.40
  4563.7 1908.23  4570.3 1908.12  4579.9 1910.57  4585.6 1916.61  4593.0 1918.51
  4808.6 1917.43  4956.1 1921.72  4990.8 1913.93  4992.4 1906.19  4992.5 1904.19
  5007.0 1904.19  5007.2 1906.19  5021.9 1920.18  5052.3 1925.97  5470.4 1926.46
  5569.6 1926.62  5647.4 1926.04  5699.1 1920.48  5928.4 1920.63  6407.2 1933.13
#Mann=5,-1,0
  2815.9    0.07       0  4992.4    0.07       0  5007.2    0.07       0
  5470.4   0.035       0  5569.6    0.07       0
Bank Sta=4992.4,5007.2
Exp/Cntr=0.3,0.1

Type RM Length L Ch R = 1,118856,1356,1356,1356
BEGIN DESCRIPTION:
Sweetwater Creek 236.0
END DESCRIPTION:
XS GIS Cut Line= 4
      1426016.49      6885035.30      1425891.33      6882851.19
      1425729.58      6882735.08      1425499.64      6879797.38
#Sta/Elev= 30
  2812.3 1936.68  3877.3 1931.10  4042.5 1929.59  4208.3 1926.83  4331.7 1923.03
  4396.8 1922.00  4726.0 1921.00  4758.8 1918.48  4863.0 1913.02  4983.2 1913.60
  4993.2 1912.88  4995.4 1902.10  4995.6 1900.10  5010.3 1902.10  5034.9 1904.97
  5057.0 1913.27  5085.2 1914.12  5868.2 1916.22  5948.5 1919.04  5968.5 1924.11
  6419.8 1922.62  6518.3 1922.13  6540.3 1929.35  6560.3 1929.29  6604.4 1920.17
  6700.8 1919.96  6771.0 1926.06  7980.8 1938.45  8129.7 1938.86  8145.8 1939.90
#Mann=14,-1,0
  2812.3    0.07       0  3877.3   0.035       0  4042.5    0.07       0
  4208.3   0.035       0  4331.7    0.07       0  4396.8   0.035       0
  4726.0    0.07       0  4758.8    0.16       0  4995.4    0.07       0
  5010.3    0.16       0  6419.8   0.035       0  6518.3    0.07       0
  7980.8   0.035       0  8129.7    0.07       0
Bank Sta=4995.4,5010.3
Exp/Cntr=0.3,0.1

Type RM Length L Ch R = 1,117500,1000,1000,1000
BEGIN DESCRIPTION:
Sweetwater Creek 234.0
END DESCRIPTION:
XS GIS Cut Line= 5
      1426764.40      6883951.60      1426305.78      6882020.86
      1426115.91      6881828.28      1425876.73      6881809.42
      1425709.27      6879832.93
#Sta/Elev= 30
  2745.1 1926.13  2854.5 1923.60  2900.1 1923.14  3033.5 1921.09  3334.7 1922.88
  3663.6 1918.30  4136.6 1923.84  4291.5 1923.82  4739.2 1912.41  4965.5 1913.03
  4986.7 1900.38  4991.2 1900.38  4991.4 1898.38  5006.0 1898.38  5006.1 1900.38
  5010.9 1907.92  5021.0 1911.15  5161.4 1910.83  5181.5 1912.72  5201.5 1921.57
  5211.6 1922.35  5369.2 1923.56  5424.9 1923.65  5515.6 1917.63  5526.3 1916.89
  5582.6 1913.95  5622.7 1914.99  5753.2 1925.42  7166.4 1935.81  7223.5 1936.83
#Mann=13,-1,0
  2745.1   0.035       0  2854.5    0.07       0  2900.1   0.035       0
  3033.5    0.07       0  4136.6   0.035       0  4291.5    0.07       0
  4991.2    0.07       0  5006.1    0.07       0  5369.2   0.035       0
  5424.9    0.07       0  5515.6   0.035       0  5526.3    0.07       0
  7166.4   0.035       0
Bank Sta=4991.2,5006.1
Exp/Cntr=0.3,0.1

Type RM Length L Ch R = 1,116500,1000,1000,1000
BEGIN DESCRIPTION:
Sweetwater Creek 232.0
END DESCRIPTION:
XS GIS Cut Line= 3
      1426971.76      6883616.78      1426638.66      6881271.92
      1426738.58      6879542.91
#Sta/Elev= 30
  2631.6 1928.29  2642.5 1928.17  2717.7 1928.57  3103.1 1918.60  3771.7 1921.99
  4478.7 1911.22  4660.5 1914.30  4731.2 1911.75  4751.5 1906.37  4761.6 1910.11
  4923.8 1911.98  4973.7 1903.83  4994.7 1907.88  4996.9 1899.66  4997.1 1897.66
  5011.9 1899.66  5013.9 1906.70  5044.0 1899.66  5084.1 1916.64  5124.1 1918.96
  5706.5 1919.80  5795.2 1919.78  5845.3 1925.70  5885.2 1920.64  5935.5 1925.73
  5965.5 1922.55  6045.7 1927.41  6296.1 1926.26  6336.1 1930.13  6731.9 1935.47
#Mann=7,-1,0
  2631.6   0.035       0  2642.5    0.07       0  2717.7   0.035       0
  3103.1    0.07       0  4996.9    0.07       0  5011.9    0.16       0
  5706.5    0.07       0
Bank Sta=4996.9,5011.9
Exp/Cntr=0.3,0.1

Type RM Length L Ch R = 1,115500,1000,1000,1000
BEGIN DESCRIPTION:
Sweetwater Creek 230.0
END DESCRIPTION:
XS GIS Cut Line= 3
      1427340.39      6884610.58      1427500.19      6881630.66
      1427353.85      6879493.66
#Sta/Elev= 30
  2015.8 1927.61  2809.4 1929.51  3075.4 1928.82  3230.1 1927.75  3520.5 1919.55
  3610.7 1921.35  3692.5 1914.71  3783.4 1917.94  4100.9 1918.03  4401.8 1917.21
  4436.6 1911.75  4483.0 1910.93  4635.2 1912.18  4808.6 1907.18  4992.1 1911.91
  4995.8 1898.40  4996.0 1896.40  5010.7 1898.40  5012.7 1902.90  5032.7 1898.40
  5052.8 1909.43  5062.8 1910.96  5159.7 1909.53  5173.1 1912.47  5258.0 1913.55
  5356.3 1919.44  5704.5 1919.51  6385.9 1921.39  7056.3 1929.52  7142.0 1931.84
#Mann=14,-1,0
  2015.8    0.07       0  2809.4   0.035       0  3075.4    0.07       0
  3783.4   0.035       0  4100.9    0.07       0  4483.0   0.035       0
  4635.2    0.07       0  4995.8    0.07       0  5010.7    0.07       0
  5159.7    0.16       0  5258.0    0.07       0  5356.3   0.035       0
  5704.5    0.07       0  7056.3   0.035       0
Bank Sta=4995.8,5010.7
Exp/Cntr=0.3,0.1

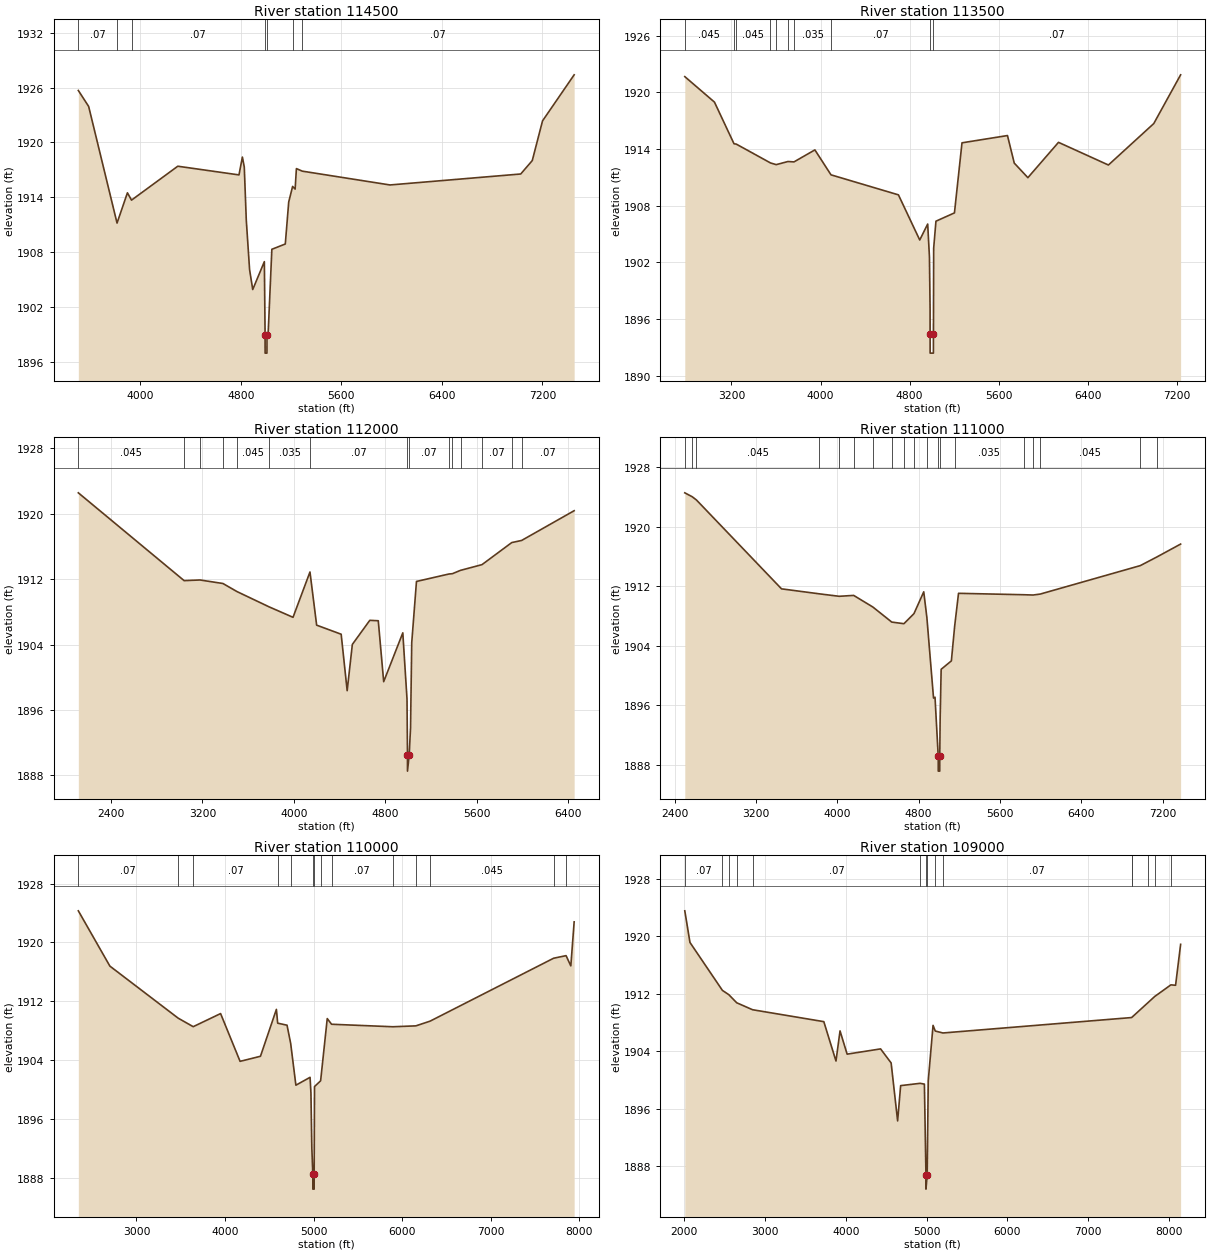
Type RM Length L Ch R = 1,114500,1000,1000,1000
BEGIN DESCRIPTION:
Sweetwater Creek 228.0
END DESCRIPTION:
XS GIS Cut Line= 3
      1428105.00      6883238.00      1428449.93      6881785.81
      1427968.40      6879381.25
#Sta/Elev= 30
  3507.4 1925.68  3589.6 1923.93  3815.4 1911.17  3898.0 1914.48  3930.6 1913.68
  4298.8 1917.39  4785.5 1916.44  4812.7 1918.39  4827.7 1917.31  4843.6 1911.52
  4869.9 1906.08  4895.0 1903.90  4987.5 1906.95  4993.3 1898.94  4993.5 1896.94
  5008.1 1896.94  5008.3 1898.94  5018.2 1899.27  5047.1 1908.30  5154.1 1908.88
  5181.3 1913.48  5212.2 1915.18  5232.3 1914.89  5242.5 1917.13  5289.6 1916.85
  5987.0 1915.34  7027.3 1916.54  7119.1 1918.01  7200.6 1922.35  7452.3 1927.39
#Mann=7,-1,0
  3507.4    0.07       0  3815.4   0.035       0  3930.6    0.07       0
  4993.3    0.07       0  5008.3    0.07       0  5212.2   0.035       0
  5289.6    0.07       0
Bank Sta=4993.3,5008.3
Exp/Cntr=0.3,0.1

Type RM Length L Ch R = 1,113500,1500,1500,1500
BEGIN DESCRIPTION:
Sweetwater Creek 225.0
END DESCRIPTION:
XS GIS Cut Line= 5
      1430043.02      6883085.03      1429375.54      6881317.00
      1429090.37      6881152.21      1428809.35      6881228.39
      1428440.44      6879321.30
#Sta/Elev= 30
  2780.8 1921.65  3047.2 1918.95  3222.8 1914.54  3243.8 1914.50  3550.3 1912.51
  3601.7 1912.33  3707.5 1912.66  3761.4 1912.62  3949.1 1913.89  4093.8 1911.25
  4699.4 1909.13  4890.7 1904.35  4962.1 1906.04  4977.9 1902.55  4983.7 1896.97
  4983.8 1894.37  4984.1 1892.37  5013.4 1892.37  5013.7 1894.37  5015.9 1903.49
  5036.3 1906.34  5202.4 1907.22  5270.2 1914.64  5678.6 1915.41  5739.7 1912.49
  5861.9 1910.95  6136.9 1914.69  6585.1 1912.29  6992.5 1916.68  7233.6 1921.84
#Mann=10,-1,0
  2780.8   0.045       0  3222.8    0.07       0  3243.8   0.045       0
  3550.3    0.07       0  3601.7   0.045       0  3707.5    0.07       0
  3761.4   0.035       0  4093.8    0.07       0  4983.8    0.07       0
  5013.7    0.07       0
Bank Sta=4983.8,5013.7
Exp/Cntr=0.3,0.1

Type RM Length L Ch R = 1,112000,1000,1000,1000
BEGIN DESCRIPTION:
Sweetwater Creek 223.0
END DESCRIPTION:
XS GIS Cut Line= 3
      1430176.51      6883173.74      1429641.00      6880337.56
      1429255.00      6878938.01
#Sta/Elev= 30
  2113.7 1922.57  3039.4 1911.82  3178.5 1911.90  3378.8 1911.47  3501.9 1910.48
  3782.9 1908.61  3992.1 1907.33  4140.4 1912.88  4198.8 1906.37  4413.4 1905.26
  4465.8 1898.35  4511.1 1904.01  4663.7 1906.96  4738.0 1906.91  4785.3 1899.45
  4952.6 1905.43  4989.4 1897.33  4993.5 1890.50  4993.7 1888.50  5008.5 1890.50
  5020.3 1893.79  5030.7 1904.22  5072.2 1911.72  5355.7 1912.63  5386.1 1912.67
  5457.8 1913.08  5645.6 1913.78  5905.9 1916.48  5992.4 1916.74  6451.8 1920.38
#Mann=15,-1,0
  2113.7   0.045       0  3039.4    0.07       0  3178.5   0.045       0
  3378.8   0.035       0  3501.9   0.045       0  3782.9   0.035       0
  4140.4    0.07       0  4993.5    0.07       0  5008.5    0.07       0
  5355.7   0.045       0  5386.1    0.07       0  5457.8   0.045       0
  5645.6    0.07       0  5905.9   0.035       0  5992.4    0.07       0
Bank Sta=4993.5,5008.5
Exp/Cntr=0.3,0.1

Type RM Length L Ch R = 1,111000,1000,1000,1000
BEGIN DESCRIPTION:
Sweetwater Creek 221.0
END DESCRIPTION:
XS GIS Cut Line= 4
      1430489.83      6883493.18      1430243.96      6881276.57
      1430276.43      6881008.93      1430057.15      6878643.37
#Sta/Elev= 30
  2500.2 1924.53  2573.4 1924.00  2614.7 1923.57  3451.2 1911.64  3823.1 1910.97
  4018.2 1910.64  4160.8 1910.76  4349.5 1909.20  4535.1 1907.18  4654.8 1906.96
  4753.5 1908.31  4849.8 1911.24  4880.6 1907.79  4946.1 1896.97  4960.6 1897.09
  4992.3 1889.17  4992.5 1887.17  5007.1 1887.17  5007.3 1889.17  5011.0 1894.12
  5021.0 1900.84  5121.5 1901.97  5153.9 1906.65  5191.8 1911.04  5831.7 1910.85
  5924.8 1910.81  5995.5 1910.94  6979.3 1914.76  7141.0 1915.91  7375.7 1917.65
#Mann=19,-1,0
  2500.2   0.035       0  2573.4    0.07       0  2614.7   0.045       0
  3823.1    0.07       0  4018.2   0.045       0  4160.8   0.035       0
  4349.5   0.045       0  4535.1    0.07       0  4654.8   0.045       0
  4753.5   0.035       0  4880.6    0.07       0  4992.3    0.07       0
  5007.3    0.07       0  5153.9   0.035       0  5831.7   0.045       0
  5924.8   0.035       0  5995.5   0.045       0  6979.3    0.07       0
  7141.0   0.045       0
Bank Sta=4992.3,5007.3
Exp/Cntr=0.3,0.1

Type RM Length L Ch R = 1,110000,1000,1000,1000
BEGIN DESCRIPTION:
Sweetwater Creek 219.0
END DESCRIPTION:
XS GIS Cut Line= 3
      1431094.04      6883444.16      1431118.97      6880788.18
      1430452.30      6877922.81
#Sta/Elev= 30
  2343.9 1924.30  2700.1 1916.79  3470.9 1909.72  3641.0 1908.56  3950.1 1910.34
  4170.1 1903.85  4400.2 1904.54  4580.2 1910.91  4594.5 1909.04  4700.2 1908.76
  4741.4 1906.28  4800.2 1900.61  4960.2 1901.68  4970.2 1899.54  4980.2 1892.09
  4991.5 1888.49  4991.7 1886.49  5006.4 1886.49  5006.5 1888.49  5010.4 1900.42
  5079.4 1901.21  5154.2 1909.66  5203.1 1908.89  5894.4 1908.55  6154.7 1908.67
  6315.2 1909.31  7710.1 1917.86  7850.5 1918.21  7904.3 1916.82  7941.9 1922.80
#Mann=14,-1,0
  2343.9    0.07       0  3470.9   0.035       0  3641.0    0.07       0
  4594.5   0.035       0  4741.4    0.07       0  4991.5    0.07       0
  5006.5    0.07       0  5079.4   0.035       0  5203.1    0.07       0
  5894.4   0.035       0  6154.7    0.07       0  6315.2   0.045       0
  7710.1   0.035       0  7850.5    0.07       0
Bank Sta=4991.5,5006.5
Exp/Cntr=0.3,0.1

Type RM Length L Ch R = 1,109000,1000,1000,1000
BEGIN DESCRIPTION:
Sweetwater Creek 217.0
END DESCRIPTION:
XS GIS Cut Line= 4
      1431767.68      6883601.79      1432038.90      6880621.21
      1431843.87      6880184.62      1431392.38      6877556.39
#Sta/Elev= 30
  2007.1 1923.57  2071.2 1919.16  2472.6 1912.48  2551.9 1911.88  2650.0 1910.75
  2846.1 1909.78  3728.0 1908.12  3878.6 1902.63  3928.8 1906.83  4016.6 1903.59
  4430.9 1904.32  4561.4 1902.36  4641.7 1894.28  4679.0 1899.20  4920.5 1899.52
  4973.1 1899.41  4992.4 1886.77  4992.6 1884.77  5007.4 1886.77  5020.9 1899.89
  5080.2 1907.60  5107.6 1906.81  5202.6 1906.54  7537.5 1908.69  7541.4 1908.72
  7737.1 1910.73  7823.4 1911.62  8024.6 1913.25  8082.4 1913.19  8144.9 1918.90
#Mann=15,-1,0
  2007.1    0.07       0  2472.6   0.035       0  2551.9    0.07       0
  2650.0   0.035       0  2846.1    0.07       0  4920.5    0.16       0
  4992.4    0.07       0  5007.4    0.16       0  5107.6   0.035       0
  5202.6    0.07       0  7537.5   0.045       0  7541.4    0.07       0
  7737.1   0.045       0  7823.4   0.035       0  8024.6    0.07       0
Bank Sta=4992.4,5007.4
Exp/Cntr=0.3,0.1

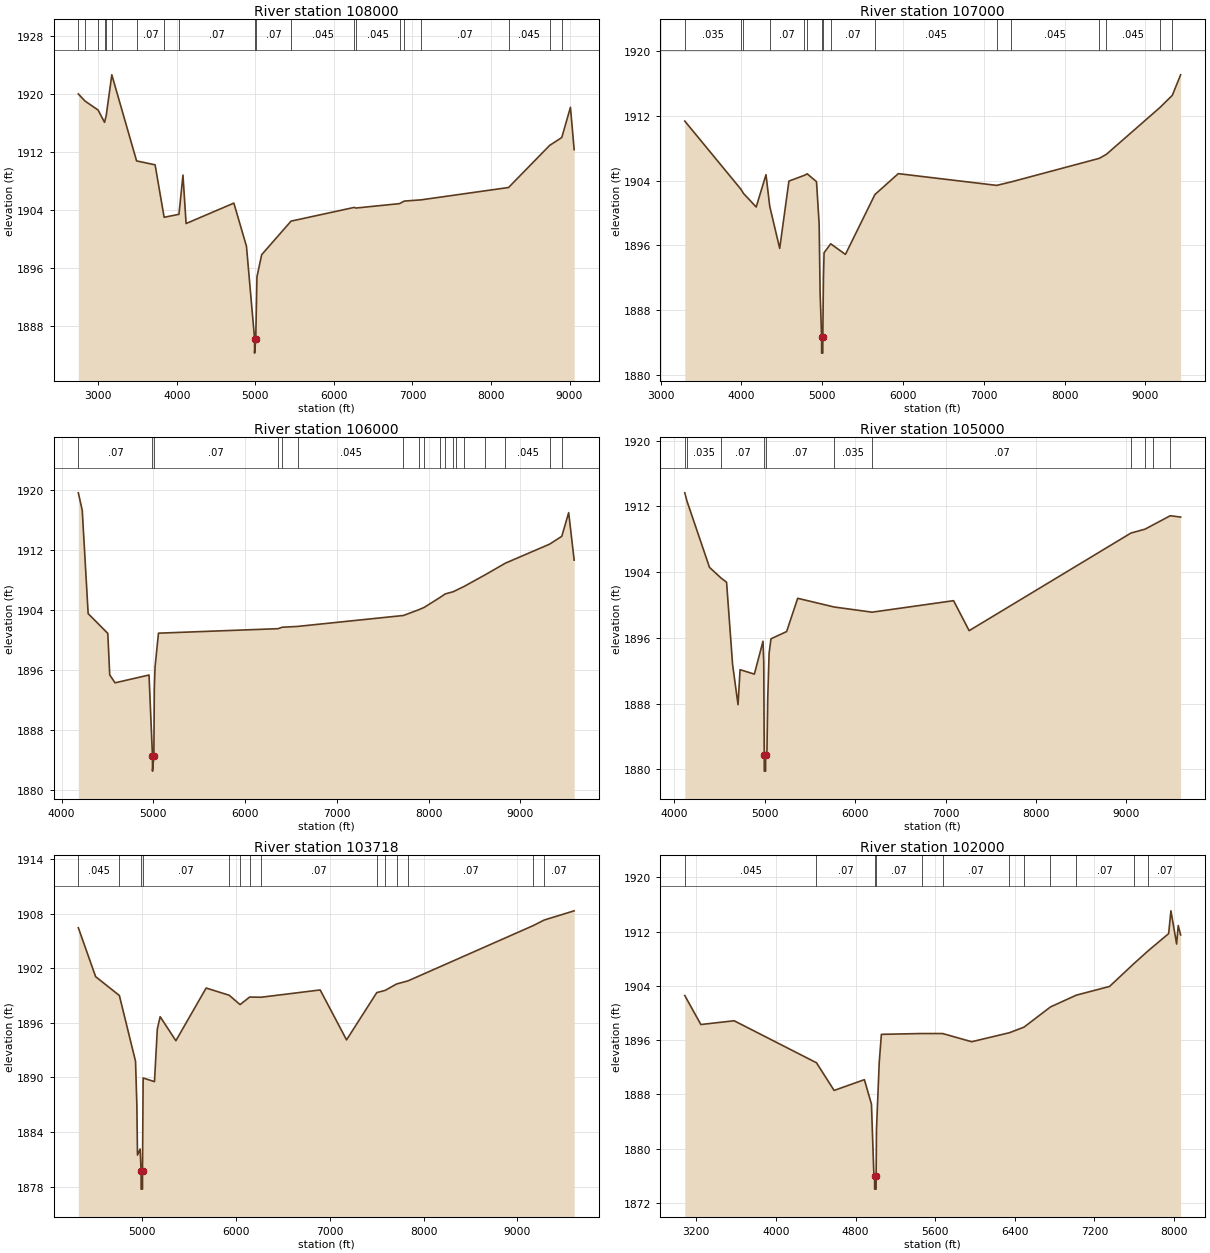
Type RM Length L Ch R = 1,108000,1000,1000,1000
BEGIN DESCRIPTION:
Sweetwater Creek 215.0
END DESCRIPTION:
XS GIS Cut Line= 5
      1432789.58      6883533.01      1432532.19      6881939.88
      1432686.07      6881318.64      1432691.39      6880924.29
      1431610.22      6877422.90
#Sta/Elev= 30
  2746.2 1919.97  2831.4 1918.99  2998.1 1917.75  3080.0 1916.06  3101.4 1917.00
  3172.6 1922.60  3487.9 1910.75  3723.7 1910.21  3838.6 1902.99  4027.4 1903.40
  4078.3 1908.80  4118.3 1902.13  4726.4 1904.94  4886.9 1899.00  4990.0 1886.29
  4990.1 1884.29  5005.0 1886.29  5020.6 1894.81  5080.6 1897.84  5454.2 1902.46
  6259.1 1904.35  6278.3 1904.26  6835.8 1904.87  6895.9 1905.22  7110.4 1905.39
  8223.6 1907.09  8746.4 1912.88  8901.3 1913.97  9011.7 1918.13  9058.9 1912.30
#Mann=20,-1,0
  2746.2    0.07       0  2831.4   0.035       0  2998.1    0.07       0
  3080.0   0.035       0  3101.4    0.07       0  3172.6   0.035       0
  3487.9    0.07       0  3838.6   0.033       0  4027.4    0.07       0
  4990.0    0.07       0  5005.0    0.07       0  5454.2   0.045       0
  6259.1    0.07       0  6278.3   0.045       0  6835.8    0.07       0
  6895.9   0.045       0  7110.4    0.07       0  8223.6   0.045       0
  8746.4   0.035       0  8901.3    0.07       0
Bank Sta=4990,5005
Exp/Cntr=0.3,0.1

Type RM Length L Ch R = 1,107000,1000,1000,1000
BEGIN DESCRIPTION:
Sweetwater Creek 213.0
END DESCRIPTION:
XS GIS Cut Line= 4
      1433882.82      6883158.41      1433421.90      6881521.46
      1433223.17      6881149.25      1431807.78      6877393.65
#Sta/Elev= 30
  3299.4 1911.36  3996.5 1902.91  4024.7 1902.44  4182.9 1900.75  4304.2 1904.74
  4350.6 1900.84  4473.8 1895.64  4588.0 1903.95  4778.7 1904.66  4813.9 1904.85
  4929.4 1903.88  4962.0 1898.66  4973.9 1890.19  4992.4 1884.71  4992.6 1882.71
  5007.3 1882.71  5007.4 1884.71  5015.3 1892.09  5023.1 1895.10  5104.8 1896.21
  5287.3 1894.90  5652.2 1902.29  5941.5 1904.87  7159.0 1903.42  7335.1 1903.84
  8429.0 1906.76  8516.2 1907.25  9181.2 1913.05  9332.6 1914.54  9435.4 1917.07
#Mann=16,-1,0
  3299.4   0.035       0  3996.5    0.07       0  4024.7   0.035       0
  4350.6    0.07       0  4778.7   0.035       0  4813.9    0.07       0
  4992.4    0.07       0  5007.4    0.07       0  5104.8    0.07       0
  5652.2   0.045       0  7159.0    0.07       0  7335.1   0.045       0
  8429.0    0.07       0  8516.2   0.045       0  9181.2   0.035       0
  9332.6    0.07       0
Bank Sta=4992.4,5007.4
Exp/Cntr=0.3,0.1

Type RM Length L Ch R = 1,106000,1000,1000,1000
BEGIN DESCRIPTION:
Sweetwater Creek 211.0
END DESCRIPTION:
XS GIS Cut Line= 3
      1434805.02      6881888.03      1434310.59      6881238.00
      1432016.36      6877266.31
#Sta/Elev= 30
  4183.3 1919.60  4226.0 1917.27  4290.4 1903.49  4504.6 1900.85  4525.4 1895.31
  4583.6 1894.26  4953.7 1895.30  4991.4 1884.48  4991.6 1882.48  5006.4 1884.48
  5011.5 1893.52  5019.2 1896.34  5056.6 1900.88  6359.8 1901.48  6403.8 1901.67
  6572.5 1901.78  7725.8 1903.24  7892.1 1904.00  7952.4 1904.32  8120.3 1905.61
  8182.2 1906.12  8269.3 1906.41  8297.1 1906.58  8384.9 1907.10  8617.7 1908.67
  8837.6 1910.22  9318.4 1912.75  9452.0 1913.80  9527.0 1916.96  9586.7 1910.62
#Mann=18,-1,0
  4183.3    0.07       0  4991.4    0.07       0  5006.4    0.07       0
  6359.8   0.035       0  6403.8    0.07       0  6572.5   0.045       0
  7725.8    0.07       0  7892.1   0.045       0  7952.4    0.07       0
  8120.3   0.045       0  8182.2    0.07       0  8269.3   0.045       0
  8297.1    0.07       0  8384.9   0.045       0  8617.7    0.07       0
  8837.6   0.045       0  9318.4   0.035       0  9452.0    0.07       0
Bank Sta=4991.4,5006.4
Exp/Cntr=0.3,0.1

Type RM Length L Ch R = 1,105000,1282,1282,1282
BEGIN DESCRIPTION:
Sweetwater Creek 209.0
END DESCRIPTION:
XS GIS Cut Line= 3
      1435587.05      6881733.62      1435200.35      6880937.91
      1432583.30      6877153.82
#Sta/Elev= 30
  4115.3 1913.65  4138.4 1912.68  4388.5 1904.58  4517.1 1903.27  4577.4 1902.77
  4644.1 1892.75  4704.3 1887.86  4726.9 1892.12  4884.8 1891.58  4980.6 1895.58
  4988.8 1893.02  4994.3 1881.77  4994.5 1879.77  5009.2 1879.77  5009.3 1881.77
  5024.2 1882.20  5033.0 1888.62  5047.9 1894.12  5068.9 1895.88  5241.9 1896.76
  5364.2 1900.81  5768.1 1899.75  6187.7 1899.12  7088.9 1900.52  7261.4 1896.87
  9050.8 1908.75  9208.2 1909.23  9299.6 1909.77  9486.3 1910.86  9600.9 1910.70
#Mann=11,-1,0
  4115.3    0.07       0  4138.4   0.035       0  4517.1    0.07       0
  4994.3    0.07       0  5009.3    0.07       0  5768.1   0.035       0
  6187.7    0.07       0  9050.8   0.045       0  9208.2    0.07       0
  9299.6   0.045       0  9486.3    0.07       0
Bank Sta=4994.3,5009.3
Exp/Cntr=0.3,0.1

Type RM Length L Ch R = 1,103718,1718,1718,1718
BEGIN DESCRIPTION:
Sweetwater Creek 206.0
END DESCRIPTION:
XS GIS Cut Line= 4
      1436405.02      6880888.02      1435955.50      6880377.80
      1435276.83      6880292.94      1433060.52      6877059.20
#Sta/Elev= 30
  4320.0 1906.46  4504.5 1901.08  4757.4 1899.01  4929.6 1891.78  4943.8 1887.00
  4950.4 1881.46  4978.9 1882.13  4989.0 1879.72  4989.1 1877.72  5003.8 1877.72
  5004.0 1879.72  5010.6 1889.94  5131.5 1889.54  5161.8 1895.32  5192.0 1896.68
  5359.7 1894.04  5682.1 1899.83  5927.5 1899.04  6043.7 1898.01  6146.0 1898.84
  6269.0 1898.82  6897.5 1899.62  7178.5 1894.13  7500.7 1899.33  7589.4 1899.57
  7712.9 1900.28  7833.9 1900.62  9164.7 1906.68  9285.7 1907.31  9604.3 1908.32
#Mann=14,-1,0
  4320.0   0.045       0  4757.4    0.07       0  4989.0    0.07       0
  5004.0    0.07       0  5927.5   0.035       0  6043.7    0.07       0
  6146.0   0.035       0  6269.0    0.07       0  7500.7   0.035       0
  7589.4    0.07       0  7712.9   0.035       0  7833.9    0.07       0
  9164.7   0.045       0  9285.7    0.07       0
Bank Sta=4989,5004
Exp/Cntr=0.3,0.1

Type RM Length L Ch R = 1,102000,1500,1500,1500
BEGIN DESCRIPTION:
Sweetwater Creek 202.0
END DESCRIPTION:
XS GIS Cut Line= 3
      1436547.90      6880777.02      1436226.97      6878888.30
      1434748.00      6876202.59
#Sta/Elev= 30
  3084.2 1902.56  3245.5 1898.29  3580.2 1898.84  4407.2 1892.65  4584.4 1888.57
  4888.7 1890.16  4959.7 1886.55  4983.5 1876.33  4991.5 1876.02  4991.6 1874.02
  5006.4 1874.02  5006.6 1876.02  5010.2 1882.82  5037.7 1892.68  5059.5 1896.84
  5463.7 1896.96  5674.6 1896.96  5966.5 1895.75  6346.1 1897.08  6493.2 1897.91
  6758.4 1900.88  7018.1 1902.62  7351.7 1903.90  7595.4 1907.25  7741.7 1909.18
  7945.7 1911.69  7968.5 1915.05  8025.8 1910.15  8041.9 1912.88  8066.0 1911.50
#Mann=12,-1,0
  3084.2   0.045       0  4407.2    0.07       0  4991.5    0.07       0
  5006.6    0.07       0  5463.7   0.035       0  5674.6    0.07       0
  6346.1   0.035       0  6493.2    0.07       0  6758.4   0.035       0
  7018.1    0.07       0  7595.4   0.035       0  7741.7    0.07       0
Bank Sta=4991.5,5006.6
Exp/Cntr=0.3,0.1

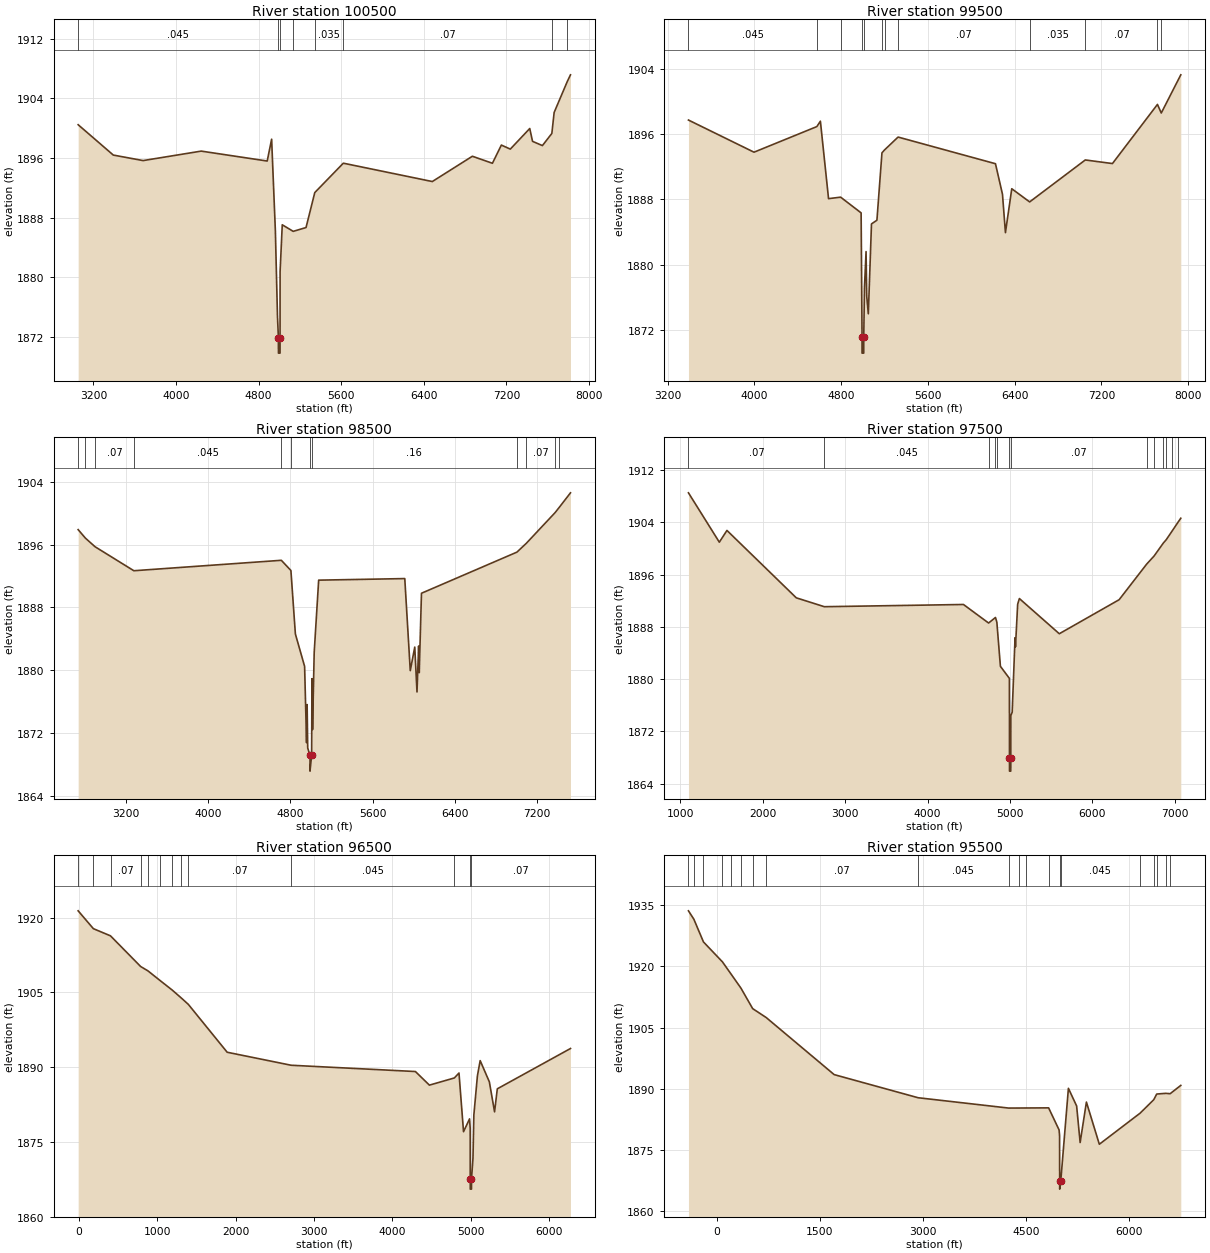
Type RM Length L Ch R = 1,100500,1000,1000,1000
BEGIN DESCRIPTION:
Sweetwater Creek 200.0
END DESCRIPTION:
XS GIS Cut Line= 3
      1436749.63      6881519.68      1437186.81      6879620.75
      1438780.38      6877293.58
#Sta/Elev= 30
  3051.4 1900.48  3391.8 1896.41  3680.6 1895.67  4243.5 1896.94  4882.7 1895.61
  4925.5 1898.54  4961.8 1886.23  4982.3 1874.71  4991.4 1871.85  4991.5 1869.85
  5007.0 1869.85  5007.1 1871.85  5007.5 1880.78  5028.5 1887.06  5134.7 1886.18
  5258.7 1886.69  5343.5 1891.38  5619.9 1895.32  6482.0 1892.86  6870.0 1896.25
  7064.3 1895.31  7150.9 1897.75  7237.6 1897.21  7425.8 1899.97  7452.9 1898.25
  7548.4 1897.68  7639.9 1899.31  7662.1 1902.12  7789.4 1906.27  7820.5 1907.17
#Mann=8,-1,0
  3051.4   0.045       0  4991.4    0.07       0  5007.1    0.07       0
  5134.7    0.07       0  5343.5   0.035       0  5619.9    0.07       0
  7639.9    0.16       0  7789.4    0.07       0
Bank Sta=4991.4,5007.1
Exp/Cntr=0.3,0.1

Type RM Length L Ch R = 1,99500,1000,1000,1000
BEGIN DESCRIPTION:
Sweetwater Creek 198.0
END DESCRIPTION:
XS GIS Cut Line= 3
      1437003.45      6881567.44      1437770.57      6880153.43
      1439517.60      6877799.50
#Sta/Elev= 30
  3391.3 1897.71  3995.8 1893.78  4575.1 1896.91  4608.0 1897.57  4683.1 1888.10
  4794.7 1888.28  4983.5 1886.36  4992.1 1871.21  4992.2 1869.21  5007.7 1869.21
  5007.8 1871.21  5014.4 1877.23  5029.0 1881.63  5035.2 1876.15  5049.9 1874.02
  5079.1 1885.01  5129.2 1885.46  5175.7 1893.70  5199.1 1894.05  5324.3 1895.63
  6222.4 1892.37  6287.1 1888.63  6314.3 1883.94  6372.7 1889.31  6537.6 1887.70
  7050.8 1892.83  7301.1 1892.39  7716.1 1899.62  7751.4 1898.57  7931.4 1903.24
#Mann=12,-1,0
  3391.3   0.045       0  4575.1    0.07       0  4794.7    0.16       0
  4992.1    0.07       0  5007.8    0.16       0  5175.7    0.07       0
  5199.1   0.035       0  5324.3    0.07       0  6537.6   0.035       0
  7050.8    0.07       0  7716.1   0.035       0  7751.4    0.07       0
Bank Sta=4992.1,5007.8
Exp/Cntr=0.3,0.1

Type RM Length L Ch R = 1,98500,1000,1000,1000
BEGIN DESCRIPTION:
Sweetwater Creek 196.0
END DESCRIPTION:
XS GIS Cut Line= 3
      1437763.87      6882321.17      1438583.34      6880209.18
      1439799.53      6877993.98
#Sta/Elev= 30
  2734.6 1897.90  2804.9 1896.82  2899.1 1895.72  3276.7 1892.66  4712.4 1893.99
  4805.6 1892.69  4849.1 1884.60  4938.9 1880.47  4958.1 1870.75  4963.4 1875.60
  4969.1 1870.07  4991.5 1869.12  4991.6 1867.12  5007.2 1869.12  5010.4 1878.90
  5016.1 1872.42  5032.2 1882.24  5075.8 1891.46  5914.0 1891.66  5967.5 1879.93
  6011.1 1882.93  6032.9 1877.21  6049.0 1883.07  6054.7 1879.67  6076.5 1889.79
  7005.4 1895.03  7096.7 1896.15  7377.4 1900.07  7419.0 1900.76  7527.1 1902.59
#Mann=12,-1,0
  2734.6    0.07       0  2804.9    0.16       0  2899.1    0.07       0
  3276.7   0.045       0  4712.4    0.07       0  4805.6    0.16       0
  4991.5    0.07       0  5007.2    0.16       0  7005.4   0.035       0
  7096.7    0.07       0  7377.4   0.035       0  7419.0    0.07       0
Bank Sta=4991.5,5007.2
Exp/Cntr=0.3,0.1

Type RM Length L Ch R = 1,97500,1000,1000,1000
BEGIN DESCRIPTION:
Sweetwater Creek 194.0
END DESCRIPTION:
XS GIS Cut Line= 4
      1437427.28      6883261.72      1439340.25      6880503.25
      1439512.68      6879988.12      1440054.99      6877988.04
#Sta/Elev= 30
  1099.9 1908.52  1474.4 1900.96  1566.9 1902.76  2407.9 1892.44  2748.5 1891.08
  4435.8 1891.42  4740.8 1888.58  4824.3 1889.43  4841.0 1888.70  4884.1 1881.95
  4993.2 1880.10  4994.2 1867.90  4994.4 1865.90  5009.8 1865.90  5010.0 1867.90
  5010.5 1874.41  5027.0 1874.93  5061.6 1886.33  5066.8 1884.94  5093.4 1891.45
  5114.1 1892.33  5598.5 1886.94  6324.2 1892.15  6658.1 1897.60  6748.8 1898.85
  6859.3 1900.81  6896.3 1901.35  6962.8 1902.59  7040.0 1904.04  7072.3 1904.63
#Mann=13,-1,0
  1099.9    0.07       0  2748.5   0.045       0  4740.8    0.07       0
  4824.3   0.045       0  4841.0    0.07       0  4994.2    0.07       0
  5010.0    0.07       0  6658.1   0.035       0  6748.8    0.07       0
  6859.3   0.035       0  6896.3    0.07       0  6962.8   0.035       0
  7040.0    0.07       0
Bank Sta=4994.2,5010
Exp/Cntr=0.3,0.1

Type RM Length L Ch R = 1,96500,1000,1000,1000
BEGIN DESCRIPTION:
Sweetwater Creek 192.0
END DESCRIPTION:
XS GIS Cut Line= 3
      1437289.49      6884250.98      1440352.94      6880286.21
      1440605.00      6879038.01
#Sta/Elev= 30
   -10.4 1921.35   183.8 1917.77   402.4 1916.33   786.9 1910.18   880.3 1909.30
  1035.4 1907.36  1189.1 1905.46  1301.5 1903.92  1395.1 1902.59  1891.5 1892.97
  2708.2 1890.36  4294.1 1889.10  4472.6 1886.37  4790.9 1887.81  4850.2 1888.80
  4908.2 1877.02  4985.1 1879.60  4993.3 1877.69  4994.0 1867.50  4994.1 1865.50
  5009.6 1865.50  5009.7 1867.50  5028.8 1871.68  5039.9 1880.37  5085.5 1888.24
  5120.6 1891.29  5237.8 1887.03  5304.2 1881.01  5339.4 1885.63  6273.4 1893.72
#Mann=13,-1,0
   -10.4    0.07       0   183.8   0.035       0   402.4    0.07       0
   786.9    0.16       0   880.3    0.07       0  1035.4    0.16       0
  1189.1    0.07       0  1301.5    0.16       0  1395.1    0.07       0
  2708.2   0.045       0  4790.9    0.07       0  4994.0    0.07       0
  5009.7    0.07       0
Bank Sta=4994,5009.7
Exp/Cntr=0.3,0.1

Type RM Length L Ch R = 1,95500,1000,1000,1000
BEGIN DESCRIPTION:
Sweetwater Creek 190.0
END DESCRIPTION:
XS GIS Cut Line= 3
      1437304.99      6884638.01      1441136.68      6880819.53
      1441882.82      6879228.05
#Sta/Elev= 30
  -409.5 1933.61  -331.1 1931.56  -190.9 1925.98    85.8 1921.09   208.8 1918.15
   354.9 1914.65   525.1 1909.64   722.3 1907.45  1711.8 1893.46  2934.3 1887.79
  4251.7 1885.26  4408.3 1885.27  4500.8 1885.28  4833.5 1885.31  4985.7 1879.91
  4992.8 1878.53  4994.5 1867.39  4994.7 1865.39  5010.3 1867.39  5121.6 1890.10
  5241.3 1885.77  5292.4 1876.81  5383.7 1886.73  5571.8 1876.39  6165.3 1884.01
  6363.6 1887.30  6407.0 1888.70  6540.7 1888.87  6602.8 1888.78  6757.7 1890.82
#Mann=20,-1,0
  -409.5   0.035       0  -331.1   0.035       0  -190.9   0.035       0
    85.8    0.07       0   208.8   0.035       0   354.9    0.07       0
   525.1   0.035       0   722.3    0.07       0  2934.3   0.045       0
  4251.7    0.07       0  4408.3    0.07       0  4500.8   0.045       0
  4833.5    0.07       0  4994.5    0.07       0  5010.3   0.045       0
  6165.3   0.035       0  6363.6    0.07       0  6407.0   0.035       0
  6540.7    0.07       0  6602.8   0.035       0
Bank Sta=4994.5,5010.3
Exp/Cntr=0.3,0.1