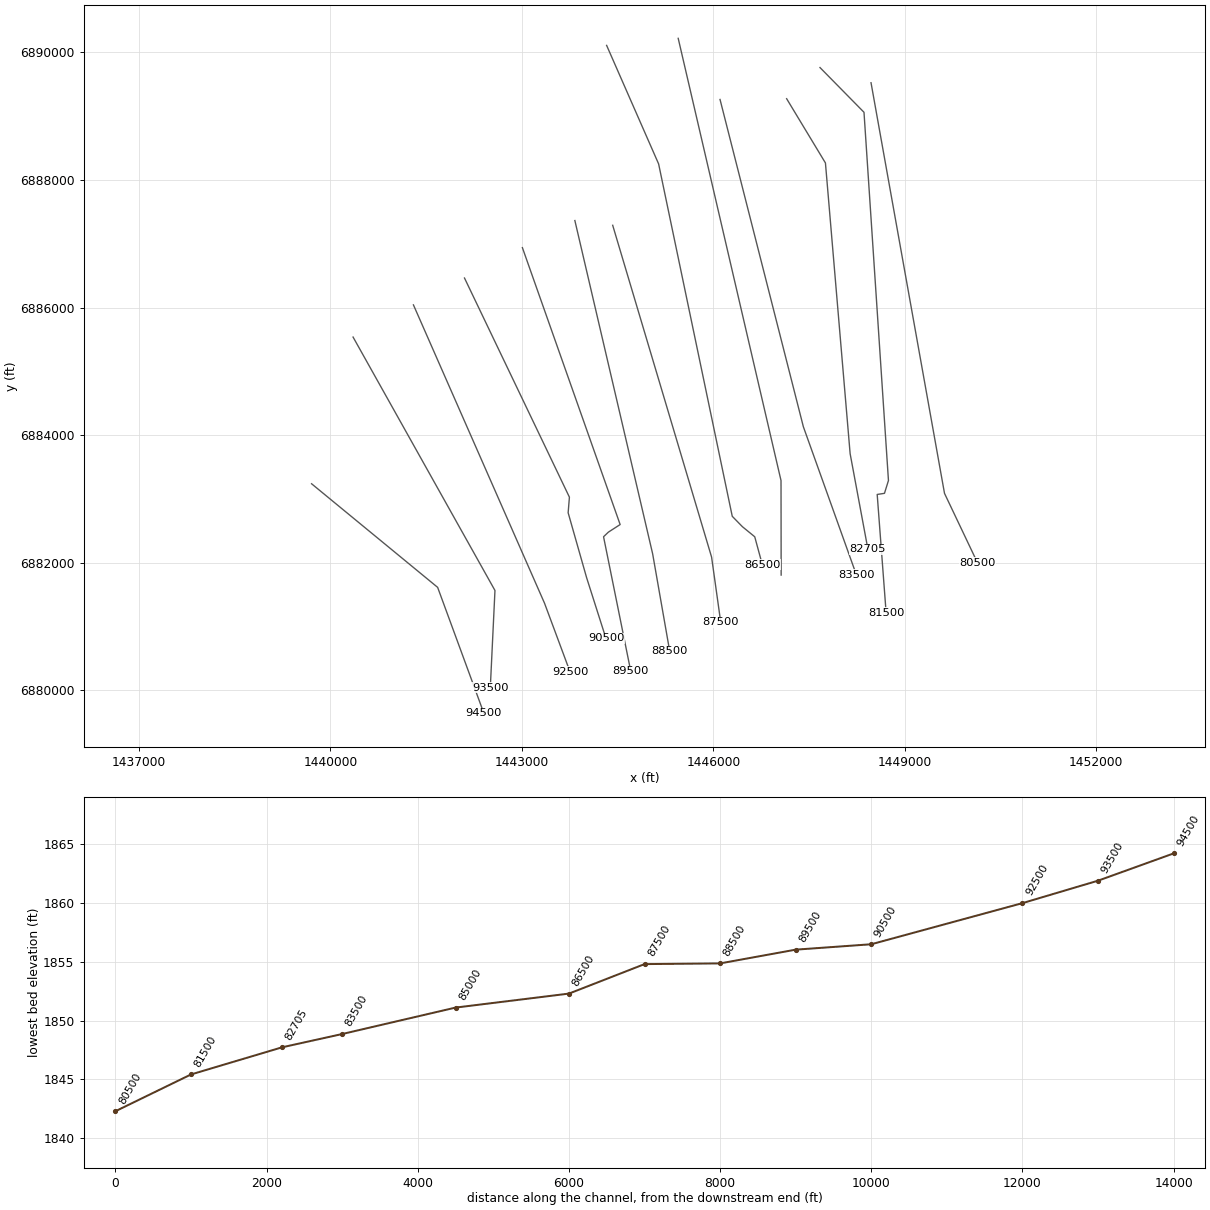
HEC-RAS study Sweetwater Creek.prj: Sweetwater Creek Base Level Engineering

--- Sweetwater Creek.g01 (geometry) --- (continued)

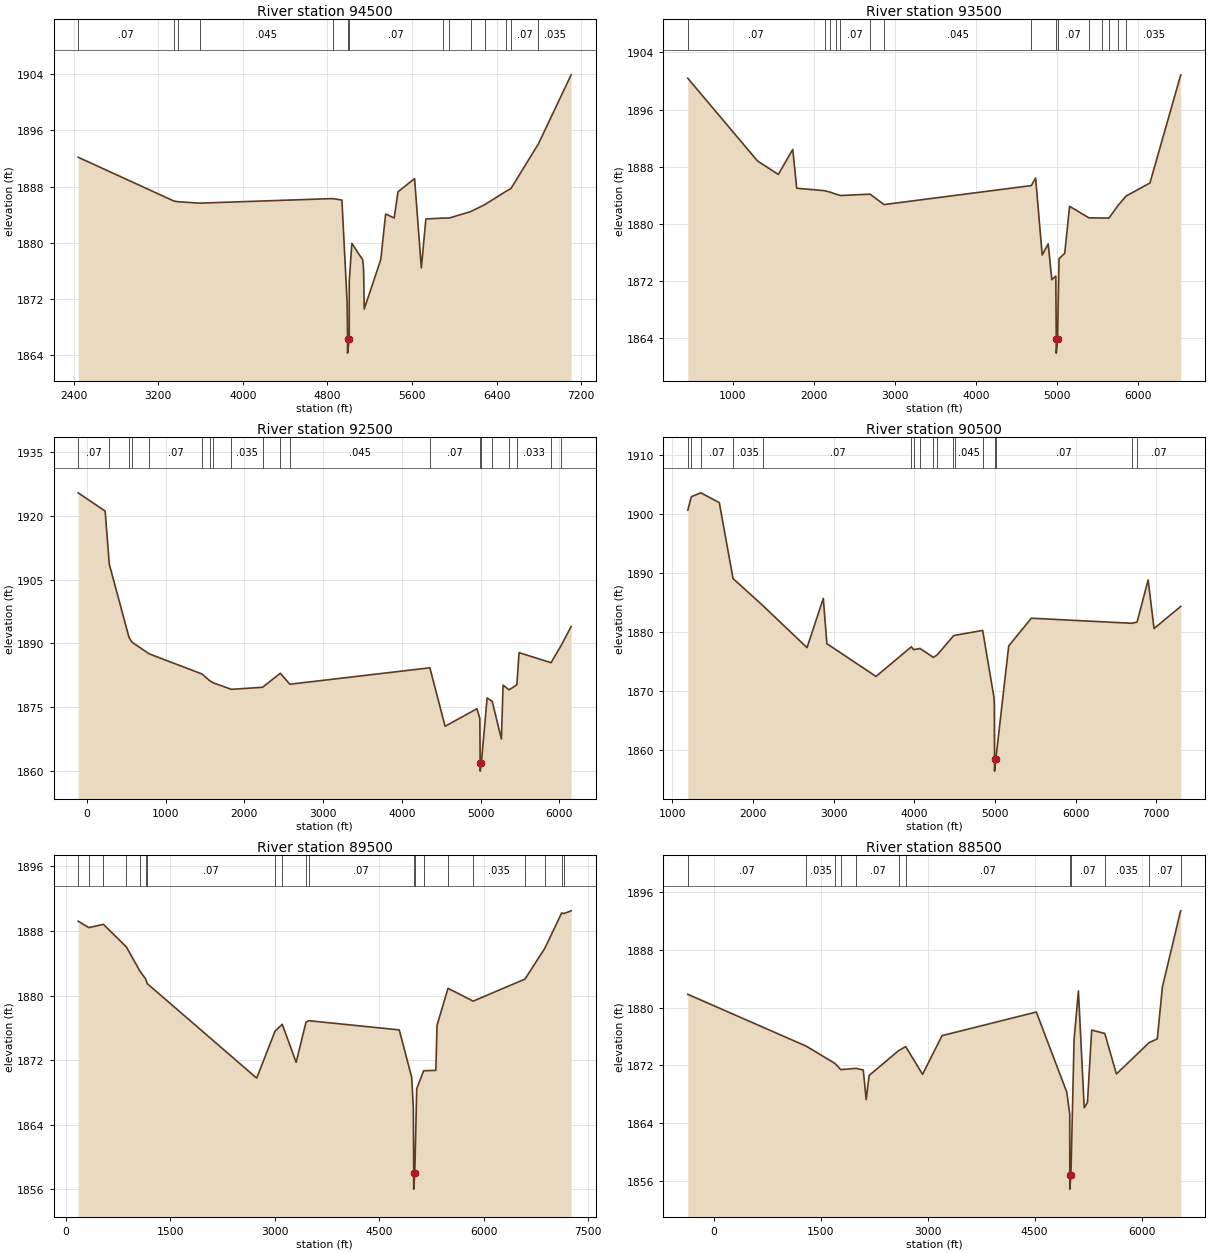
Type RM Length L Ch R = 1,94500,1000,1000,1000
BEGIN DESCRIPTION:
Sweetwater Creek 188.0
END DESCRIPTION:
XS GIS Cut Line= 3
      1439704.97      6883238.02      1441680.05      6881613.73
      1442404.99      6879638.03
#Sta/Elev= 30
  2442.8 1892.18  3346.5 1885.94  3382.0 1885.84  3592.2 1885.63  4847.8 1886.28
  4936.7 1886.07  4986.2 1871.44  4990.1 1866.23  4990.2 1864.23  5005.9 1866.23
  5006.1 1874.51  5030.8 1879.90  5133.9 1877.52  5142.1 1876.07  5147.5 1870.51
  5304.4 1877.59  5350.3 1884.08  5431.1 1883.51  5466.9 1887.25  5623.9 1889.13
  5687.8 1876.40  5730.7 1883.37  5891.4 1883.50  5950.0 1883.50  6153.5 1884.42
  6286.5 1885.41  6493.0 1887.36  6534.6 1887.70  6794.9 1894.09  7104.5 1903.94
#Mann=14,-1,0
  2442.8    0.07       0  3346.5   0.045       0  3382.0    0.07       0
  3592.2   0.045       0  4847.8    0.07       0  4990.1    0.07       0
  5005.9    0.07       0  5891.4   0.035       0  5950.0    0.07       0
  6153.5   0.035       0  6286.5    0.07       0  6493.0   0.035       0
  6534.6    0.07       0  6794.9   0.035       0
Bank Sta=4990.1,5005.9
Exp/Cntr=0.3,0.1

Type RM Length L Ch R = 1,93500,1000,1000,1000
BEGIN DESCRIPTION:
Sweetwater Creek 186.0
END DESCRIPTION:
XS GIS Cut Line= 3
      1440355.02      6885537.96      1442578.15      6881564.96
      1442505.00      6880038.01
#Sta/Elev= 30
   447.3 1900.38  1306.7 1888.81  1563.9 1886.92  1742.0 1890.42  1791.2 1884.99
  2137.4 1884.64  2205.7 1884.43  2274.5 1884.16  2330.2 1883.97  2695.5 1884.16
  2868.6 1882.70  4685.3 1885.36  4738.1 1886.42  4819.2 1875.64  4893.4 1877.20
  4937.9 1872.19  4987.0 1872.69  4992.8 1863.91  4993.0 1861.91  5008.6 1863.91
  5027.0 1875.13  5097.1 1875.88  5157.1 1882.46  5394.2 1880.85  5553.9 1880.82
  5643.0 1880.81  5756.7 1882.61  5854.8 1883.90  6148.3 1885.72  6528.7 1900.86
#Mann=15,-1,0
   447.3    0.07       0  2137.4   0.035       0  2205.7    0.07       0
  2274.5   0.035       0  2330.2    0.07       0  2695.5   0.035       0
  2868.6   0.045       0  4685.3    0.07       0  4992.8    0.07       0
  5008.6    0.07       0  5394.2   0.035       0  5553.9    0.07       0
  5643.0   0.035       0  5756.7    0.07       0  5854.8   0.035       0
Bank Sta=4992.8,5008.6
Exp/Cntr=0.3,0.1

Type RM Length L Ch R = 1,92500,2000,2000,2000
BEGIN DESCRIPTION:
Sweetwater Creek 183.0
END DESCRIPTION:
XS GIS Cut Line= 3
      1441300.71      6886042.42      1443354.98      6881364.40
      1443754.99      6880288.02
#Sta/Elev= 30
  -109.2 1925.37   233.0 1921.08   285.7 1908.61   535.4 1891.45   572.0 1890.31
   793.9 1887.53  1461.2 1882.83  1560.3 1881.24  1605.8 1880.73  1836.0 1879.21
  2231.8 1879.70  2456.2 1882.99  2577.6 1880.41  4354.9 1884.27  4548.3 1870.54
  4952.4 1874.65  4989.1 1872.41  4993.4 1862.00  4993.6 1860.00  5009.2 1862.00
  5081.5 1877.21  5146.6 1876.38  5262.9 1867.55  5284.2 1880.20  5360.7 1879.09
  5459.3 1880.27  5486.9 1887.83  5892.8 1885.47  6025.6 1889.65  6148.3 1893.98
#Mann=20,-1,0
  -109.2    0.07       0   285.7   0.035       0   535.4    0.07       0
   572.0   0.035       0   793.9    0.07       0  1461.2   0.035       0
  1560.3    0.07       0  1605.8   0.035       0  1836.0   0.035       0
  2231.8    0.07       0  2456.2   0.035       0  2577.6   0.045       0
  4354.9    0.07       0  4993.4    0.07       0  5009.2    0.07       0
  5146.6    0.16       0  5360.7    0.07       0  5459.3   0.033       0
  5892.8    0.07       0  6025.6   0.035       0
Bank Sta=4993.4,5009.2
Exp/Cntr=0.3,0.1

Type RM Length L Ch R = 1,90500,1000,1000,1000
BEGIN DESCRIPTION:
Sweetwater Creek 180.0
END DESCRIPTION:
XS GIS Cut Line= 5
      1442100.62      6886463.66      1443744.53      6883027.78
      1443724.79      6882783.23      1444014.24      6881764.79
      1444317.64      6880812.47
#Sta/Elev= 30
  1191.1 1900.65  1234.8 1902.93  1352.8 1903.58  1581.7 1901.92  1752.0 1889.08
  2127.5 1884.43  2669.4 1877.39  2871.3 1885.72  2915.7 1878.06  3524.8 1872.52
  3963.4 1877.53  3991.6 1877.04  4070.5 1877.25  4235.6 1875.74  4284.7 1876.18
  4479.5 1879.30  4499.0 1879.47  4847.5 1880.30  4986.3 1869.05  4991.9 1867.74
  4994.1 1858.50  4994.2 1856.50  5009.9 1858.50  5170.3 1877.68  5450.4 1882.37
  6696.4 1881.51  6761.6 1881.71  6899.0 1888.84  6972.4 1880.62  7303.6 1884.37
#Mann=17,-1,0
  1191.1    0.07       0  1234.8   0.035       0  1352.8    0.07       0
  1752.0   0.035       0  2127.5    0.07       0  3963.4   0.035       0
  3991.6    0.07       0  4070.5   0.045       0  4235.6    0.07       0
  4284.7   0.045       0  4479.5    0.07       0  4499.0   0.045       0
  4847.5    0.07       0  4994.1    0.07       0  5009.9    0.07       0
  6696.4    0.16       0  6761.6    0.07       0
Bank Sta=4994.1,5009.9
Exp/Cntr=0.3,0.1

Type RM Length L Ch R = 1,89500,1000,1000,1000
BEGIN DESCRIPTION:
Sweetwater Creek 178.0
END DESCRIPTION:
XS GIS Cut Line= 5
      1443007.83      6886940.09      1444539.39      6882598.64
      1444355.02      6882479.48      1444279.52      6882407.20
      1444705.18      6880301.10
#Sta/Elev= 30
   176.8 1889.21   330.1 1888.41   538.9 1888.82   868.7 1886.02  1067.1 1882.97
  1145.0 1882.07  1167.1 1881.49  2739.1 1869.78  3003.3 1875.61  3106.2 1876.44
  3305.7 1871.74  3447.3 1876.72  3486.3 1876.89  4785.7 1875.75  4964.3 1869.88
  4987.8 1866.06  4992.9 1858.04  4993.1 1856.04  5008.7 1858.04  5036.5 1868.47
  5135.4 1870.69  5310.9 1870.74  5328.2 1876.33  5485.6 1880.90  5846.3 1879.31
  6590.6 1882.04  6876.0 1885.87  7118.4 1890.24  7146.2 1890.15  7253.2 1890.49
#Mann=20,-1,0
   176.8    0.07       0   330.1   0.035       0   538.9    0.07       0
   868.7   0.035       0  1067.1    0.07       0  1145.0   0.035       0
  1167.1    0.07       0  3003.3   0.035       0  3106.2    0.07       0
  3447.3   0.045       0  3486.3    0.07       0  4992.9    0.07       0
  5008.7    0.16       0  5135.4    0.07       0  5485.6    0.07       0
  5846.3   0.035       0  6590.6   0.035       0  6876.0    0.07       0
  7118.4   0.035       0  7146.2    0.07       0
Bank Sta=4992.9,5008.7
Exp/Cntr=0.3,0.1

Type RM Length L Ch R = 1,88500,1000,1000,1000
BEGIN DESCRIPTION:
Sweetwater Creek 176.0
END DESCRIPTION:
XS GIS Cut Line= 3
      1443830.00      6887364.92      1445048.53      6882140.13
      1445315.73      6880613.95
#Sta/Elev= 30
  -365.0 1881.84  1295.1 1874.67  1696.7 1872.29  1780.3 1871.42  1996.0 1871.59
  2095.8 1871.36  2137.3 1867.27  2178.4 1870.61  2591.6 1874.04  2691.5 1874.60
  2928.0 1870.76  3200.7 1876.12  4523.4 1879.39  4950.8 1868.29  4991.9 1865.25
  4992.9 1856.87  4993.0 1854.87  5008.7 1856.87  5052.9 1875.54  5113.8 1882.32
  5195.1 1866.14  5240.6 1866.85  5300.0 1876.89  5483.7 1876.42  5646.6 1870.81
  6105.1 1875.15  6220.4 1875.68  6291.5 1882.84  6546.8 1893.38  6549.4 1893.40
#Mann=12,-1,0
  -365.0    0.07       0  1295.1   0.035       0  1696.7    0.07       0
  1780.3   0.035       0  1996.0    0.07       0  2591.6   0.035       0
  2691.5    0.07       0  4992.9    0.07       0  5008.7    0.07       0
  5483.7   0.035       0  6105.1    0.07       0  6546.8   0.035       0
Bank Sta=4992.9,5008.7
Exp/Cntr=0.3,0.1

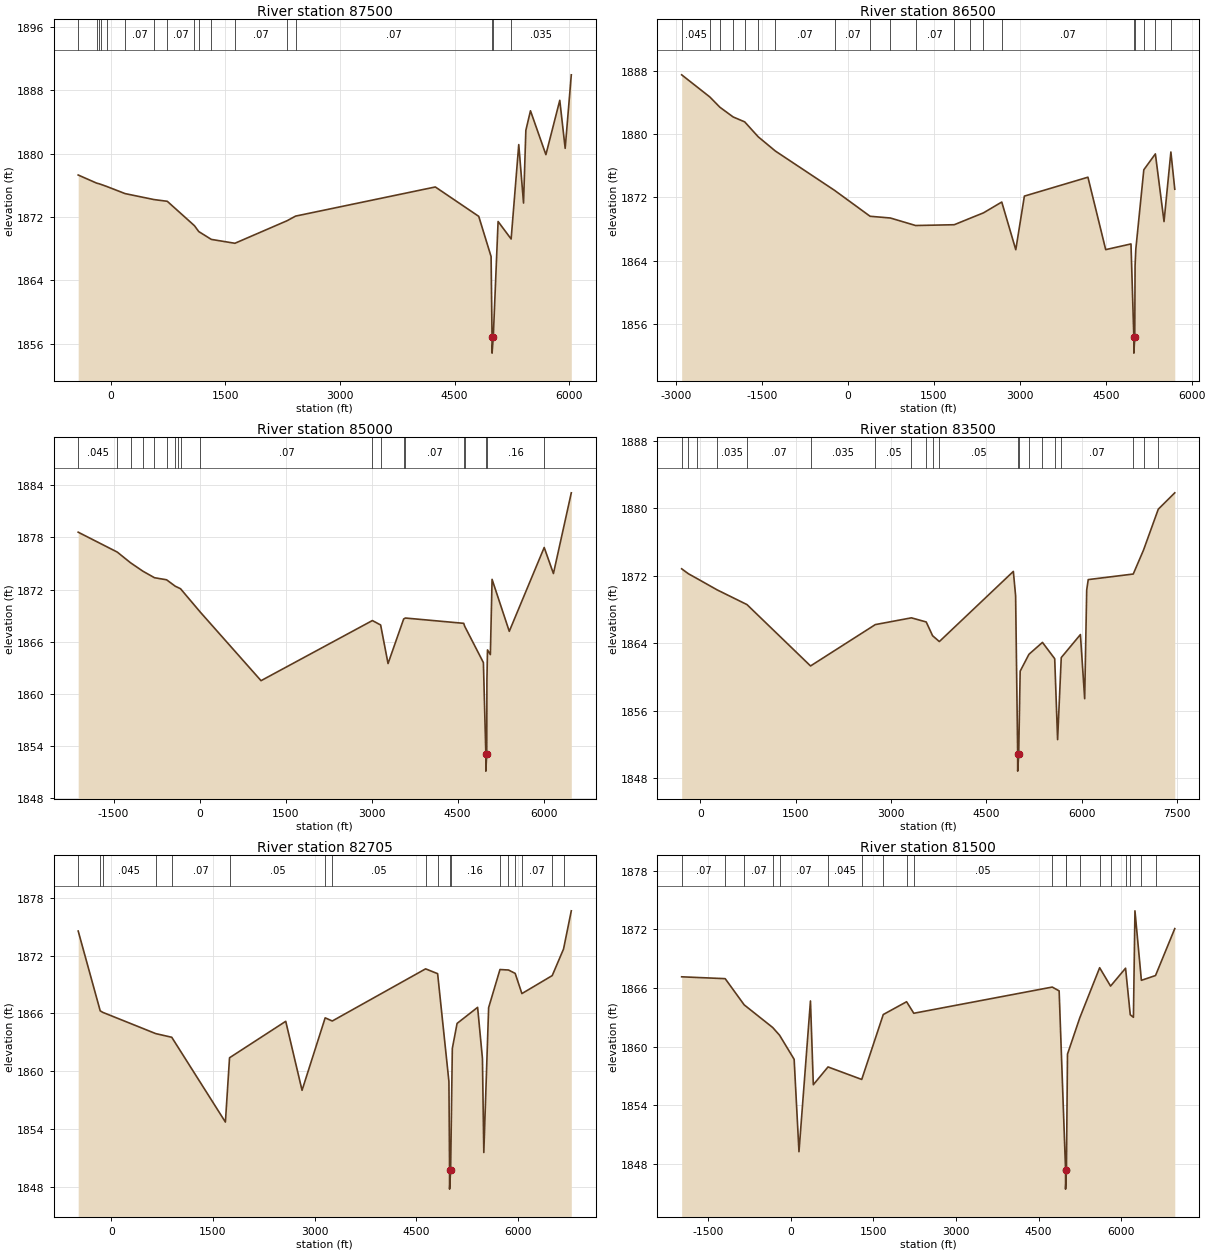
Type RM Length L Ch R = 1,87500,1000,1000,1000
BEGIN DESCRIPTION:
Sweetwater Creek 174.0
END DESCRIPTION:
XS GIS Cut Line= 3
      1444422.73      6887290.44      1445972.14      6882088.17
      1446115.16      6881068.55
#Sta/Elev= 30
  -428.1 1877.30  -187.6 1876.28  -156.2 1876.20  -125.6 1876.10   -56.1 1875.86
   187.1 1874.95   564.7 1874.20   738.7 1873.98  1094.5 1870.90  1150.5 1870.16
  1315.4 1869.17  1624.1 1868.68  2308.0 1871.53  2418.3 1872.11  4248.9 1875.79
  4817.5 1872.08  4979.3 1867.00  4991.8 1856.81  4992.0 1854.81  5007.7 1856.81
  5070.9 1871.43  5241.7 1869.22  5341.5 1881.14  5404.1 1873.76  5434.4 1882.94
  5495.0 1885.41  5696.9 1879.87  5878.7 1886.73  5949.4 1880.67  6029.6 1889.95
#Mann=17,-1,0
  -428.1   0.035       0  -187.6    0.07       0  -156.2   0.035       0
  -125.6    0.07       0   -56.1   0.035       0   187.1    0.07       0
   564.7   0.035       0   738.7    0.07       0  1094.5   0.035       0
  1150.5    0.07       0  1315.4   0.035       0  1624.1    0.07       0
  2308.0   0.035       0  2418.3    0.07       0  4991.8    0.07       0
  5007.7    0.07       0  5241.7   0.035       0
Bank Sta=4991.8,5007.7
Exp/Cntr=0.3,0.1

Type RM Length L Ch R = 1,86500,1500,1500,1500
BEGIN DESCRIPTION:
Sweetwater Creek 171.0
END DESCRIPTION:
XS GIS Cut Line= 6
      1444327.60      6890111.03      1445142.23      6888252.73
      1446295.95      6882727.86      1446454.99      6882564.86
      1446648.17      6882407.00      1446767.71      6881967.03
#Sta/Elev= 30
 -2900.8 1887.50 -2409.2 1884.70 -2233.6 1883.40 -2002.1 1882.17 -1800.8 1881.55
 -1564.6 1879.66 -1265.3 1877.86  -232.8 1872.89   387.7 1869.61   741.9 1869.39
  1182.9 1868.44  1856.4 1868.54  2130.4 1869.35  2366.3 1870.04  2685.9 1871.41
  2930.6 1865.38  3080.6 1872.16  4189.8 1874.55  4500.0 1865.39  4941.1 1866.11
  4991.2 1854.30  4991.3 1852.30  5007.0 1854.30  5012.6 1863.35  5025.8 1865.47
  5165.1 1875.49  5366.9 1877.50  5517.9 1868.94  5637.6 1877.74  5705.4 1873.03
#Mann=20,-1,0
 -2900.8   0.045       0 -2409.2    0.07       0 -2233.6   0.045       0
 -2002.1   0.035       0 -1800.8   0.045       0 -1564.6    0.07       0
 -1265.3    0.07       0  -232.8    0.07       0   387.7   0.035       0
   741.9   0.035       0  1182.9    0.07       0  1856.4   0.035       0
  2130.4    0.07       0  2366.3   0.035       0  2685.9    0.07       0
  4991.2    0.07       0  5007.0    0.07       0  5165.1    0.07       0
  5366.9    0.07       0  5637.6    0.07       0
Bank Sta=4991.2,5007
Exp/Cntr=0.3,0.1

Type RM Length L Ch R = 1,85000,1500,1500,1500
BEGIN DESCRIPTION:
Sweetwater Creek 168.0
END DESCRIPTION:
XS GIS Cut Line= 3
      1445449.03      6890221.67      1447059.93      6883288.04
      1447062.14      6881806.44
#Sta/Elev= 30
 -2118.3 1878.61 -1436.9 1876.32 -1205.5 1875.09  -987.4 1874.11  -787.7 1873.37
  -576.6 1873.13  -425.1 1872.39  -383.3 1872.26  -333.5 1872.10    11.3 1869.41
  1070.4 1861.52  3012.7 1868.44  3156.3 1867.93  3285.6 1863.49  3558.0 1868.62
  3588.0 1868.73  4605.4 1868.12  4621.8 1867.79  4948.7 1863.60  4991.1 1853.11
  4991.2 1851.11  5006.9 1853.11  5010.0 1861.55  5020.0 1865.06  5070.0 1864.52
  5100.0 1873.18  5400.0 1867.20  6009.1 1876.85  6170.0 1873.85  6481.6 1883.14
#Mann=19,-1,0
 -2118.3   0.045       0 -1436.9   0.035       0 -1205.5    0.07       0
  -987.4   0.035       0  -787.7   0.045       0  -576.6    0.07       0
  -425.1   0.045       0  -383.3    0.07       0  -333.5   0.045       0
    11.3    0.07       0  3012.7   0.035       0  3156.3    0.07       0
  3558.0    0.05       0  3588.0    0.07       0  4605.4   0.035       0
  4621.8    0.07       0  4991.1    0.07       0  5006.9    0.16       0
  6009.1   0.035       0
Bank Sta=4991.1,5006.9
Exp/Cntr=0.3,0.1

Type RM Length L Ch R = 1,83500,795,795,795
BEGIN DESCRIPTION:
Sweetwater Creek 166.0
END DESCRIPTION:
XS GIS Cut Line= 3
      1446104.42      6889263.15      1447409.90      6884132.22
      1448239.33      6881813.51
#Sta/Elev= 30
  -294.4 1872.83  -187.9 1872.24   -58.8 1871.70   264.3 1870.33   733.0 1868.59
  1733.0 1861.32  2752.0 1866.22  3320.0 1867.02  3552.7 1866.53  3653.0 1864.90
  3759.2 1864.21  4923.1 1872.52  4958.9 1869.63  4991.5 1850.86  4991.6 1848.86
  5007.3 1850.86  5030.5 1860.70  5168.5 1862.70  5381.3 1864.11  5573.8 1862.18
  5619.5 1852.59  5676.8 1862.31  5978.2 1865.04  6045.3 1857.44  6077.2 1870.32
  6101.3 1871.55  6809.4 1872.21  6971.0 1875.05  7203.1 1879.89  7462.6 1881.83
#Mann=20,-1,0
  -294.4   0.035       0  -187.9   0.035       0   -58.8    0.07       0
   264.3   0.035       0   733.0    0.07       0  1733.0   0.035       0
  2752.0    0.05       0  3320.0    0.07       0  3552.7   0.035       0
  3653.0    0.07       0  3759.2    0.05       0  4991.5    0.07       0
  5007.3   0.035       0  5168.5    0.16       0  5381.3    0.07       0
  5573.8    0.16       0  5676.8    0.07       0  6809.4    0.07       0
  6971.0   0.035       0  7203.1   0.035       0
Bank Sta=4991.5,5007.3
Exp/Cntr=0.3,0.1

Type RM Length L Ch R = 1,82705,1205,1205,1205
BEGIN DESCRIPTION:
Sweetwater Creek 164.0
END DESCRIPTION:
XS GIS Cut Line= 4
      1447147.96      6889275.14      1447755.95      6888267.77
      1448142.80      6883709.25      1448421.92      6882208.51
#Sta/Elev= 30
  -487.8 1874.55  -163.0 1866.26  -125.3 1866.10   657.0 1863.89   893.1 1863.51
  1685.0 1854.70  1746.0 1861.38  2575.4 1865.17  2816.2 1858.00  3157.5 1865.53
  3262.2 1865.20  4639.9 1870.62  4817.2 1870.12  4984.0 1858.91  4993.5 1849.73
  4993.7 1847.73  5009.3 1849.73  5034.2 1862.35  5104.4 1864.95  5407.4 1866.62
  5478.6 1861.32  5498.9 1851.54  5570.1 1866.59  5737.5 1870.55  5862.8 1870.50
  5961.9 1870.15  6061.0 1868.05  6508.7 1869.92  6675.6 1872.68  6790.2 1876.65
#Mann=18,-1,0
  -487.8   0.045       0  -163.0    0.07       0  -125.3   0.045       0
   657.0    0.07       0   893.1    0.07       0  1746.0    0.05       0
  3157.5   0.035       0  3262.2    0.05       0  4639.9    0.07       0
  4817.2    0.16       0  4993.5    0.07       0  5009.3    0.16       0
  5737.5   0.035       0  5862.8    0.07       0  5961.9   0.035       0
  6061.0    0.07       0  6508.7   0.035       0  6675.6    0.07       0
Bank Sta=4993.5,5009.3
Exp/Cntr=0.3,0.1

Type RM Length L Ch R = 1,81500,1000,1000,1000
BEGIN DESCRIPTION:
Sweetwater Creek 162.0
END DESCRIPTION:
XS GIS Cut Line= 6
      1447670.60      6889763.48      1448360.02      6889062.23
      1448743.27      6883289.14      1448680.84      6883087.99
      1448566.80      6883070.49      1448706.69      6881216.93
#Sta/Elev= 30
 -1979.8 1867.14 -1189.5 1866.95  -844.4 1864.27  -326.0 1861.95  -201.6 1861.16
    62.6 1858.70   150.3 1849.25   358.9 1864.67   410.9 1856.10   677.6 1857.92
  1289.7 1856.64  1680.8 1863.28  2104.5 1864.59  2235.2 1863.41  4748.9 1866.09
  4874.3 1865.70  4991.0 1847.42  4991.2 1845.42  5006.9 1847.42  5026.1 1859.23
  5248.4 1862.93  5610.2 1868.07  5808.3 1866.19  6080.6 1868.02  6166.0 1863.26
  6223.5 1863.00  6251.1 1873.89  6367.9 1866.78  6624.6 1867.27  6974.2 1872.07
#Mann=20,-1,0
 -1979.8    0.07       0 -1189.5   0.035       0  -844.4    0.07       0
  -326.0   0.035       0  -201.6    0.07       0   677.6   0.045       0
  1289.7    0.07       0  1680.8   0.045       0  2104.5   0.035       0
  2235.2    0.05       0  4748.9    0.07       0  4991.0    0.07       0
  5006.9    0.16       0  5248.4   0.035       0  5610.2   0.035       0
  5808.3   0.035       0  6080.6    0.07       0  6166.0   0.035       0
  6367.9    0.07       0  6624.6   0.035       0
Bank Sta=4991,5006.9
Exp/Cntr=0.3,0.1

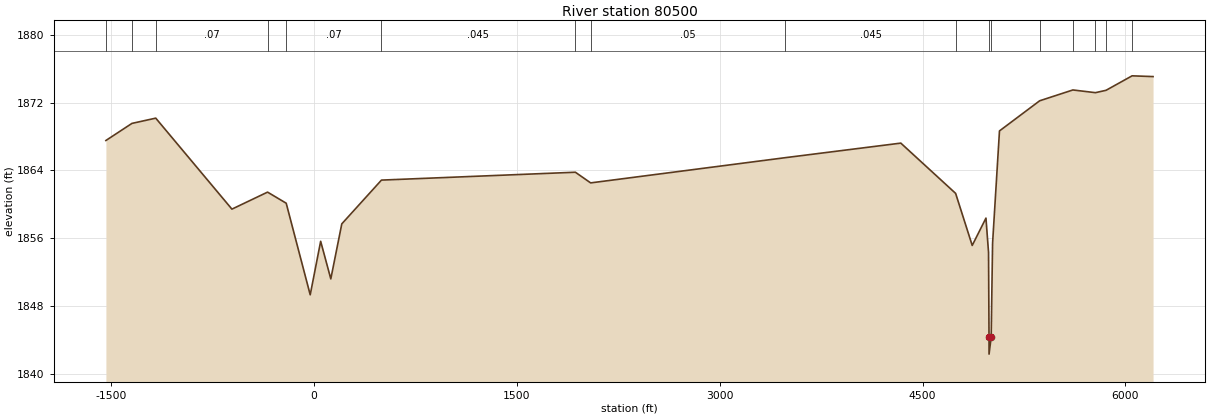
Type RM Length L Ch R = 1,80500,1000,1000,1000
BEGIN DESCRIPTION:
Sweetwater Creek 160.0
END DESCRIPTION:
XS GIS Cut Line= 3
      1448470.20      6889525.57      1449621.40      6883087.59
      1450138.35      6881999.11
#Sta/Elev= 30
 -1540.1 1867.53 -1347.3 1869.55 -1171.4 1870.17  -608.0 1859.42  -344.4 1861.43
  -206.5 1860.12   -28.9 1849.30    48.4 1855.62   123.4 1851.18   204.7 1857.68
   498.0 1862.85  1932.3 1863.78  2045.3 1862.52  3484.8 1865.50  4339.3 1867.22
  4744.8 1861.28  4867.5 1855.13  4969.1 1858.36  4988.2 1854.31  4991.8 1844.29
  4992.0 1842.29  5007.7 1844.29  5018.1 1855.40  5069.1 1868.66  5366.3 1872.22
  5611.8 1873.50  5779.0 1873.18  5857.3 1873.46  6050.0 1875.17  6205.0 1875.08
#Mann=17,-1,0
 -1540.1    0.07       0 -1347.3   0.035       0 -1171.4    0.07       0
  -344.4   0.035       0  -206.5    0.07       0   498.0   0.045       0
  1932.3   0.035       0  2045.3    0.05       0  3484.8   0.045       0
  4744.8    0.07       0  4991.8    0.07       0  5007.7    0.07       0
  5366.3   0.035       0  5611.8   0.045       0  5779.0   0.035       0
  5857.3   0.045       0  6050.0    0.07       0
Bank Sta=4991.8,5007.7
Exp/Cntr=0.3,0.1