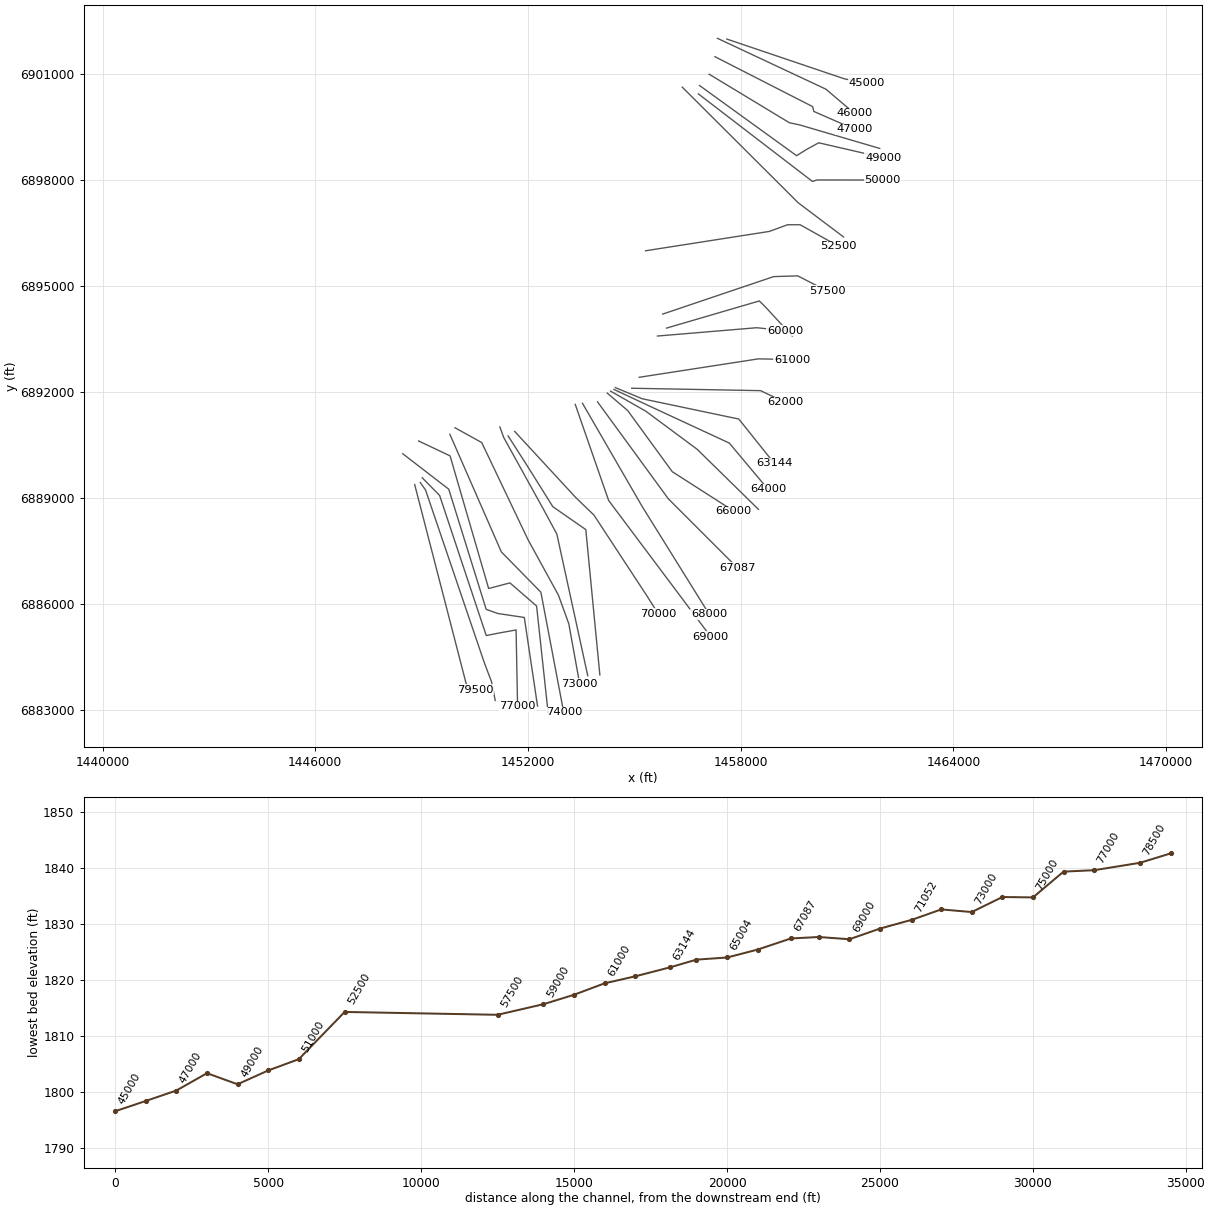
HEC-RAS study Sweetwater Creek.prj: Sweetwater Creek Base Level Engineering

--- Sweetwater Creek.g01 (geometry) --- (continued)

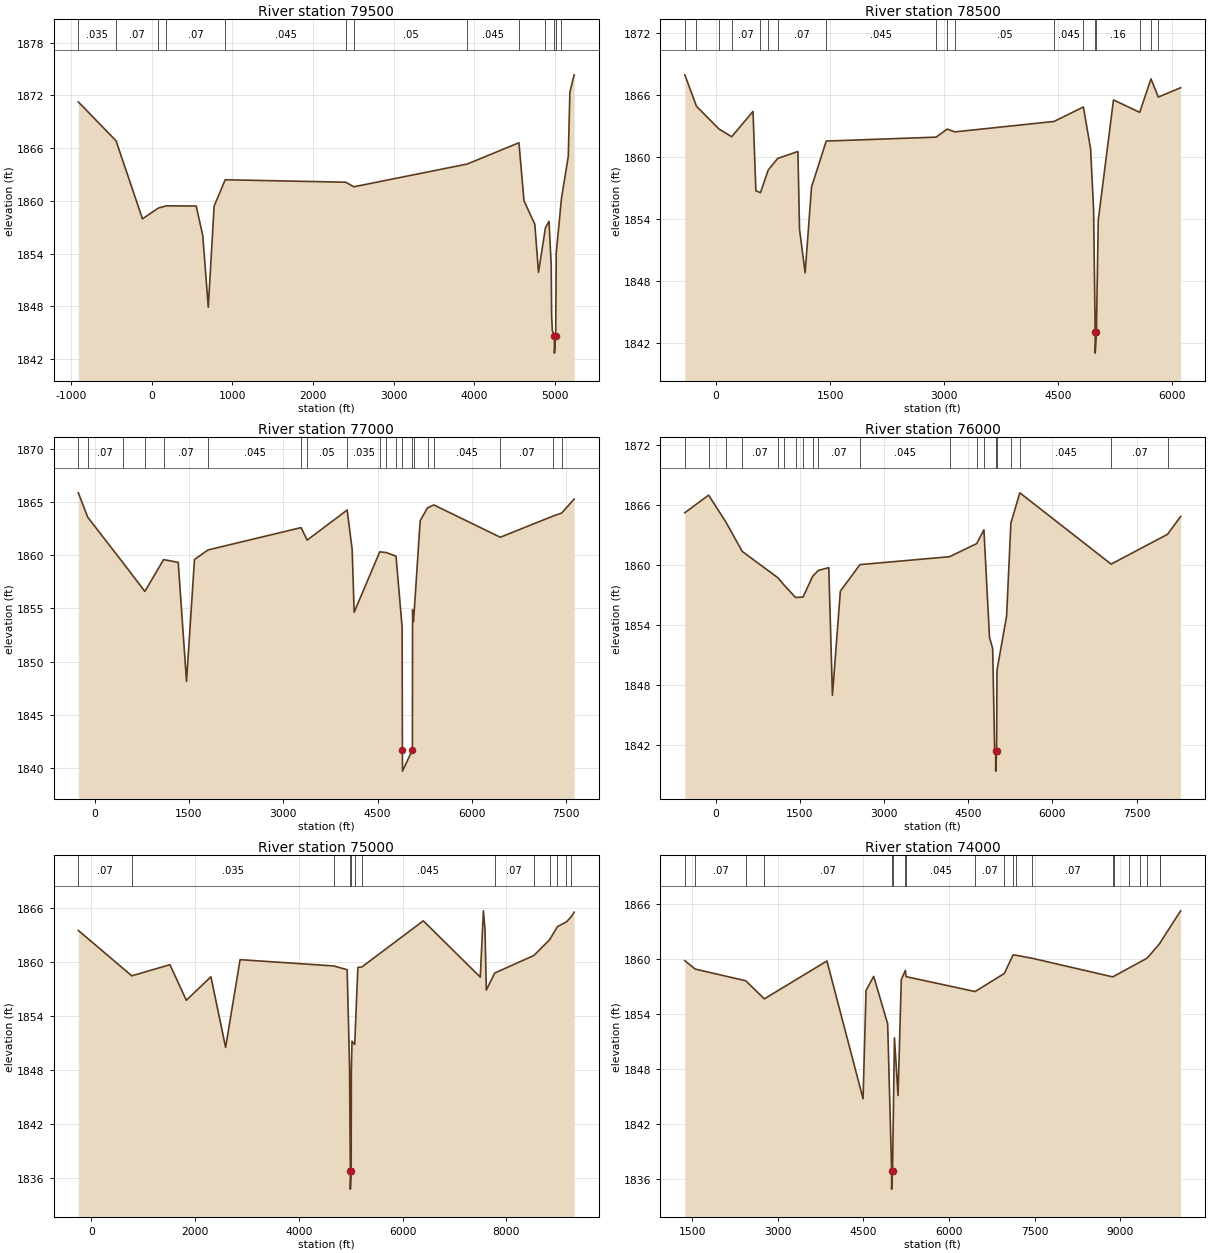
Type RM Length L Ch R = 1,79500,1000,1000,1000
BEGIN DESCRIPTION:
Sweetwater Creek 157.0
END DESCRIPTION:
XS GIS Cut Line= 3
      1448804.99      6889388.04      1450281.76      6883664.79
      1450505.02      6883587.99
#Sta/Elev= 30
  -910.7 1871.26  -442.9 1866.83  -115.4 1857.95    79.7 1859.17   180.1 1859.43
   550.5 1859.41   631.8 1856.06   700.4 1847.89   772.7 1859.40   910.3 1862.40
  2404.0 1862.12  2505.0 1861.60  3911.3 1864.19  4551.4 1866.61  4614.6 1860.00
  4748.2 1857.34  4794.1 1851.86  4880.0 1856.93  4924.4 1857.67  4951.6 1852.69
  4956.7 1846.98  4965.7 1845.22  4991.3 1844.67  4991.5 1842.67  5007.2 1844.67
  5014.0 1854.07  5078.8 1860.27  5163.3 1865.05  5183.2 1872.37  5236.1 1874.34
#Mann=13,-1,0
  -910.7   0.035       0  -442.9    0.07       0    79.7   0.035       0
   180.1    0.07       0   910.3   0.045       0  2404.0   0.035       0
  2505.0    0.05       0  3911.3   0.045       0  4551.4    0.07       0
  4880.0    0.16       0  4991.3    0.07       0  5007.2    0.16       0
  5078.8    0.07       0
Bank Sta=4991.3,5007.2
Exp/Cntr=0.3,0.1

Type RM Length L Ch R = 1,78500,1500,1500,1500
BEGIN DESCRIPTION:
Sweetwater Creek 156.0
END DESCRIPTION:
XS GIS Cut Line= 5
      1448962.27      6889444.65      1449111.84      6889233.93
      1450768.79      6884352.70      1450974.03      6883810.36
      1451077.19      6883283.74
#Sta/Elev= 30
  -413.2 1867.92  -259.2 1864.88    35.1 1862.69   204.2 1861.93   485.1 1864.38
   523.0 1856.70   583.2 1856.52   685.6 1858.71   810.0 1859.83  1076.5 1860.50
  1097.6 1852.98  1171.5 1848.76  1256.0 1857.07  1449.5 1861.51  2897.2 1861.89
  3041.6 1862.67  3144.0 1862.40  4450.5 1863.41  4835.9 1864.81  4931.0 1860.76
  4970.3 1854.90  4991.5 1842.99  4991.7 1840.99  5007.4 1842.99  5031.7 1853.84
  5232.2 1865.49  5577.8 1864.29  5726.2 1867.53  5822.4 1865.77  6116.5 1866.67
#Mann=18,-1,0
  -413.2   0.035       0  -259.2    0.07       0    35.1   0.035       0
   204.2    0.07       0   583.2   0.035       0   685.6    0.16       0
   810.0    0.07       0  1449.5   0.045       0  2897.2   0.035       0
  3041.6   0.045       0  3144.0    0.05       0  4450.5   0.045       0
  4835.9    0.16       0  4991.5    0.07       0  5007.4    0.16       0
  5577.8   0.035       0  5726.2    0.07       0  5822.4   0.045       0
Bank Sta=4991.5,5007.4
Exp/Cntr=0.3,0.1

Type RM Length L Ch R = 1,77000,1000,1000,1000
BEGIN DESCRIPTION:
Sweetwater Creek 153.0
END DESCRIPTION:
XS GIS Cut Line= 6
      1449017.53      6889580.29      1449508.33      6889081.45
      1450824.11      6885119.24      1451199.46      6885193.52
      1451665.74      6885277.10      1451707.81      6883124.43
#Sta/Elev= 30
  -257.4 1865.91  -107.7 1863.61   448.6 1859.35   800.5 1856.61  1098.3 1859.61
  1331.0 1859.35  1463.0 1848.12  1589.6 1859.62  1802.7 1860.52  3284.8 1862.63
  3381.6 1861.45  4017.4 1864.29  4096.9 1860.55  4128.6 1854.65  4535.4 1860.34
  4636.5 1860.28  4794.1 1859.94  4891.3 1853.24  4895.8 1841.66  4897.3 1839.66
  5054.4 1841.66  5057.6 1854.88  5072.7 1853.76  5178.3 1863.28  5294.9 1864.49
  5395.0 1864.77  6452.4 1861.72  7287.2 1863.71  7428.0 1864.00  7626.8 1865.32
#Mann=20,-1,0
  -257.4   0.035       0  -107.7    0.07       0   448.6   0.035       0
   800.5    0.07       0  1098.3    0.07       0  1802.7   0.045       0
  3284.8   0.035       0  3381.6    0.05       0  4017.4   0.035       0
  4535.4    0.05       0  4636.5   0.035       0  4794.1    0.07       0
  4895.8    0.07       0  5054.4    0.07       0  5072.7   0.035       0
  5294.9    0.07       0  5395.0   0.045       0  6452.4    0.07       0
  7287.2    0.16       0  7428.0    0.07       0
Bank Sta=4895.8,5054.4
Exp/Cntr=0.3,0.1

Type RM Length L Ch R = 1,76000,1000,1000,1000
BEGIN DESCRIPTION:
Sweetwater Creek 151.0
END DESCRIPTION:
XS GIS Cut Line= 6
      1448467.07      6890260.84      1449766.43      6889257.23
      1450822.21      6885860.13      1451153.54      6885741.89
      1451897.41      6885630.37      1452271.04      6883125.87
#Sta/Elev= 30
  -551.0 1865.21  -127.0 1866.97   180.6 1864.29   472.3 1861.35  1105.7 1858.73
  1218.8 1857.99  1422.1 1856.75  1555.5 1856.79  1727.0 1858.86  1828.7 1859.45
  2014.7 1859.73  2079.8 1846.99  2221.0 1857.38  2569.8 1860.03  4166.7 1860.82
  4650.5 1862.13  4779.3 1863.51  4878.6 1852.77  4934.9 1851.66  4971.0 1841.41
  4989.2 1841.41  4989.3 1839.41  5005.0 1841.41  5011.6 1849.46  5183.5 1854.90
  5259.8 1864.18  5419.3 1867.20  7046.2 1860.08  8051.5 1863.06  8284.4 1864.84
#Mann=20,-1,0
  -551.0    0.07       0  -127.0   0.035       0   180.6   0.035       0
   472.3    0.07       0  1105.7   0.035       0  1218.8    0.07       0
  1422.1   0.035       0  1555.5    0.07       0  1727.0   0.035       0
  1828.7    0.07       0  2569.8   0.045       0  4166.7    0.05       0
  4650.5   0.035       0  4779.3    0.07       0  4989.2    0.07       0
  5005.0    0.07       0  5259.8    0.07       0  5419.3   0.045       0
  7046.2    0.07       0  8051.5    0.05       0
Bank Sta=4989.2,5005
Exp/Cntr=0.3,0.1

Type RM Length L Ch R = 1,75000,1000,1000,1000
BEGIN DESCRIPTION:
Sweetwater Creek 149.0
END DESCRIPTION:
XS GIS Cut Line= 6
      1448915.85      6890620.76      1449803.90      6890199.55
      1450891.56      6886449.00      1451492.35      6886607.96
      1452244.15      6885954.61      1452571.36      6882918.44
#Sta/Elev= 30
  -252.9 1863.51   779.1 1858.47  1512.5 1859.71  1829.5 1855.76  2303.8 1858.37
  2586.5 1850.53  2865.5 1860.27  4670.4 1859.57  4930.0 1859.15  4976.0 1848.46
  4991.3 1836.79  4991.5 1834.79  5007.2 1836.79  5010.9 1847.83  5023.3 1851.21
  5075.6 1850.85  5136.2 1859.40  5214.5 1859.46  6397.9 1864.58  7496.5 1858.33
  7556.9 1865.69  7587.0 1863.69  7613.1 1856.89  7773.9 1858.78  8529.2 1860.73
  8833.9 1862.49  8984.9 1863.94  9156.5 1864.46  9243.9 1864.99  9306.5 1865.54
#Mann=13,-1,0
  -252.9    0.07       0   779.1   0.035       0  4670.4    0.07       0
  4991.3    0.07       0  5007.2    0.07       0  5075.6    0.07       0
  5214.5   0.045       0  7773.9    0.07       0  8529.2    0.05       0
  8833.9    0.07       0  8984.9    0.05       0  9156.5    0.07       0
  9243.9    0.05       0
Bank Sta=4991.3,5007.2
Exp/Cntr=0.3,0.1

Type RM Length L Ch R = 1,74000,1000,1000,1000
BEGIN DESCRIPTION:
Sweetwater Creek 147.0
END DESCRIPTION:
XS GIS Cut Line= 4
      1449798.02      6890809.53      1451250.48      6887483.22
      1452365.16      6886344.94      1453010.00      6882943.49
#Sta/Elev= 30
  1370.4 1859.82  1553.7 1858.90  2437.1 1857.63  2763.5 1855.65  3860.0 1859.79
  4492.8 1844.74  4545.5 1856.57  4678.9 1858.11  4923.8 1852.92  4993.5 1836.86
  4993.6 1834.86  5009.3 1836.86  5042.2 1851.40  5105.8 1845.09  5162.4 1857.75
  5234.3 1858.76  5246.4 1858.08  6455.4 1856.45  6968.0 1858.43  7120.0 1860.45
  7166.3 1860.42  7453.7 1860.09  8866.0 1858.05  8883.9 1858.11  9159.7 1859.05
  9347.2 1859.69  9468.2 1860.10  9687.3 1861.68  9700.2 1861.83 10055.2 1865.27
#Mann=20,-1,0
  1370.4   0.035       0  1553.7    0.07       0  2437.1   0.035       0
  2763.5    0.07       0  4993.5    0.07       0  5009.3    0.07       0
  5234.3    0.07       0  5246.4   0.045       0  6455.4    0.07       0
  6968.0   0.035       0  7120.0   0.045       0  7166.3   0.035       0
  7453.7    0.07       0  8866.0    0.05       0  8883.9    0.07       0
  9159.7    0.05       0  9347.2    0.07       0  9468.2    0.05       0
  9687.3    0.07       0  9700.2    0.05       0
Bank Sta=4993.5,5009.3
Exp/Cntr=0.3,0.1

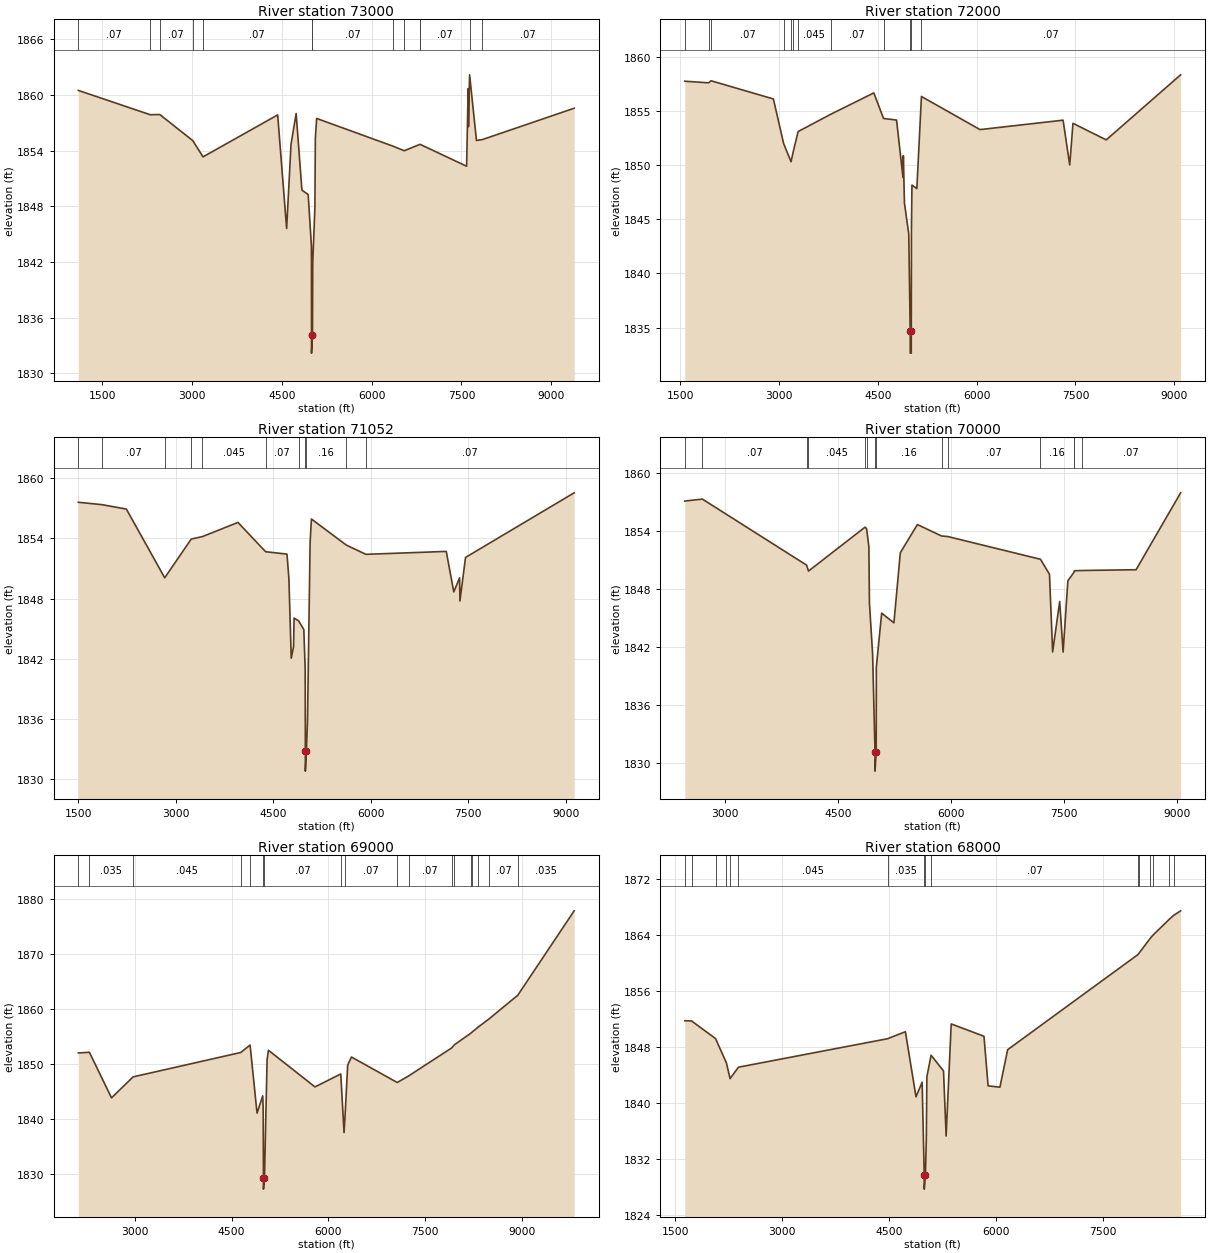
Type RM Length L Ch R = 1,73000,1000,1000,1000
BEGIN DESCRIPTION:
Sweetwater Creek 145.0
END DESCRIPTION:
XS GIS Cut Line= 6
      1449941.74      6890994.23      1450696.59      6890575.69
      1452000.65      6887833.05      1452861.35      6886259.88
      1453153.33      6885450.54      1453460.31      6883749.65
#Sta/Elev= 30
  1100.0 1860.48  2301.2 1857.86  2461.2 1857.88  3011.6 1855.07  3183.1 1853.32
  4429.8 1857.84  4579.3 1845.60  4653.0 1854.68  4738.3 1857.99  4834.7 1849.74
  4939.2 1849.26  4993.7 1843.68  4994.9 1834.17  4995.0 1832.17  5010.9 1834.17
  5015.5 1841.93  5051.4 1847.83  5059.1 1855.35  5080.9 1857.46  6348.5 1854.49
  6544.1 1853.98  6804.0 1854.66  6808.0 1854.67  7586.0 1852.31  7611.4 1860.67
  7616.7 1856.57  7635.6 1862.16  7750.1 1855.09  7848.1 1855.18  9382.0 1858.56
#Mann=13,-1,0
  1100.0    0.07       0  2301.2   0.035       0  2461.2    0.07       0
  3011.6   0.035       0  3183.1    0.07       0  4994.9    0.07       0
  5010.9    0.07       0  6348.5    0.16       0  6544.1    0.07       0
  6804.0    0.16       0  6808.0    0.07       0  7635.6    0.16       0
  7848.1    0.07       0
Bank Sta=4994.9,5010.9
Exp/Cntr=0.3,0.1

Type RM Length L Ch R = 1,72000,948,948,948
BEGIN DESCRIPTION:
Sweetwater Creek 143.0
END DESCRIPTION:
XS GIS Cut Line= 5
      1451208.07      6891016.00      1451319.69      6890713.47
      1452455.49      6888656.97      1452815.78      6887987.53
      1453687.49      6883984.14
#Sta/Elev= 30
  1568.0 1857.76  1929.9 1857.61  1967.2 1857.80  2913.4 1856.12  3068.9 1852.00
  3181.4 1850.32  3217.2 1851.32  3289.2 1853.11  3782.4 1854.70  4438.3 1856.68
  4585.6 1854.32  4783.7 1854.17  4881.3 1848.86  4886.9 1850.88  4903.2 1846.51
  4968.9 1843.65  4991.1 1834.64  4991.2 1832.64  5006.9 1832.64  5007.1 1834.64
  5009.8 1844.14  5017.4 1848.16  5091.6 1847.84  5161.4 1856.35  6051.2 1853.29
  7312.5 1854.16  7413.3 1850.02  7462.4 1853.87  7967.5 1852.34  9097.2 1858.35
#Mann=12,-1,0
  1568.0    0.07       0  1929.9   0.035       0  1967.2    0.07       0
  3068.9   0.035       0  3181.4   0.045       0  3217.2   0.035       0
  3289.2   0.045       0  3782.4    0.07       0  4585.6   0.045       0
  4991.1   0.045       0  5007.1   0.045       0  5161.4    0.07       0
Bank Sta=4991.1,5007.1
Exp/Cntr=0.3,0.1

Type RM Length L Ch R = 1,71052,1052,1052,1052
BEGIN DESCRIPTION:
Sweetwater Creek 141.0
END DESCRIPTION:
XS GIS Cut Line= 5
      1451440.68      6890763.18      1451991.92      6889900.20
      1452701.71      6888762.93      1453632.50      6888114.65
      1454028.83      6884004.62
#Sta/Elev= 30
  1501.1 1857.60  1865.4 1857.36  2239.9 1856.92  2830.0 1850.07  3237.9 1853.93
  3411.3 1854.18  3957.1 1855.59  4382.6 1852.67  4711.1 1852.43  4740.7 1849.98
  4776.5 1842.06  4812.3 1843.20  4820.2 1846.06  4891.2 1845.77  4970.2 1844.91
  4991.2 1840.96  4993.7 1832.80  4993.8 1830.80  5009.7 1832.80  5026.8 1835.87
  5067.0 1853.60  5087.1 1855.93  5624.3 1853.33  5924.6 1852.41  7161.7 1852.70
  7277.2 1848.67  7366.4 1850.07  7371.4 1847.76  7458.0 1852.10  9129.1 1858.54
#Mann=11,-1,0
  1501.1   0.035       0  1865.4    0.07       0  2830.0   0.045       0
  3237.9    0.07       0  3411.3   0.045       0  4382.6    0.07       0
  4891.2    0.16       0  4993.7    0.07       0  5009.7    0.16       0
  5624.3   0.035       0  5924.6    0.07       0
Bank Sta=4993.7,5009.7
Exp/Cntr=0.3,0.1

Type RM Length L Ch R = 1,70000,1000,1000,1000
BEGIN DESCRIPTION:
Sweetwater Creek 139.0
END DESCRIPTION:
XS GIS Cut Line= 6
      1451626.45      6890890.58      1453343.63      6889026.86
      1453863.38      6888523.21      1454742.40      6887179.54
      1455355.27      6886242.80      1455673.33      6885739.48
#Sta/Elev= 30
  2465.8 1857.13  2699.7 1857.33  4082.7 1850.50  4107.0 1849.89  4857.3 1854.43
  4877.6 1854.28  4908.1 1852.40  4915.5 1846.61  4957.7 1841.30  4989.4 1831.21
  4989.6 1829.21  5005.4 1831.21  5007.2 1839.99  5077.9 1845.54  5240.5 1844.54
  5325.4 1851.79  5551.8 1854.70  5871.9 1853.52  5955.7 1853.46  7185.0 1851.11
  7304.1 1849.56  7346.2 1841.53  7439.7 1846.75  7485.0 1841.52  7548.3 1848.88
  7630.4 1849.78  7632.7 1849.92  7729.8 1849.95  8453.2 1850.03  9044.2 1857.98
#Mann=14,-1,0
  2465.8   0.035       0  2699.7    0.07       0  4082.7   0.035       0
  4107.0   0.045       0  4857.3    0.16       0  4877.6    0.07       0
  4989.4    0.07       0  5005.4    0.16       0  5871.9   0.035       0
  5955.7    0.07       0  7185.0    0.16       0  7630.4    0.07       0
  7632.7    0.16       0  7729.8    0.07       0
Bank Sta=4989.4,5005.4
Exp/Cntr=0.3,0.1

Type RM Length L Ch R = 1,69000,1000,1000,1000
BEGIN DESCRIPTION:
Sweetwater Creek 137.0
END DESCRIPTION:
XS GIS Cut Line= 4
      1453334.88      6891653.95      1453449.16      6891324.33
      1454276.61      6888937.98      1457154.98      6885088.02
#Sta/Elev= 30
  2125.4 1852.04  2296.8 1852.16  2639.7 1843.88  2973.6 1847.69  4640.2 1852.12
  4786.6 1853.47  4894.1 1841.11  4982.0 1844.25  4989.4 1841.90  4993.3 1829.30
  4993.4 1827.30  5009.3 1829.30  5049.7 1850.78  5070.6 1852.53  5791.7 1845.87
  6191.1 1848.22  6241.9 1837.57  6258.2 1840.71  6298.5 1849.84  6356.5 1851.30
  7066.6 1846.67  7243.0 1847.87  7908.1 1852.94  7949.8 1853.51  8201.7 1855.59
  8230.1 1855.87  8321.5 1856.75  8490.2 1858.24  8934.0 1862.53  9807.0 1877.86
#Mann=18,-1,0
  2125.4    0.07       0  2296.8   0.035       0  2973.6   0.045       0
  4640.2   0.035       0  4786.6    0.07       0  4993.3    0.07       0
  5009.3    0.07       0  6191.1    0.16       0  6258.2    0.07       0
  7066.6    0.16       0  7243.0    0.07       0  7908.1   0.035       0
  7949.8    0.07       0  8201.7   0.035       0  8230.1    0.07       0
  8321.5   0.035       0  8490.2    0.07       0  8934.0   0.035       0
Bank Sta=4993.3,5009.3
Exp/Cntr=0.3,0.1

Type RM Length L Ch R = 1,68000,913,913,913
BEGIN DESCRIPTION:
Sweetwater Creek 135.0
END DESCRIPTION:
XS GIS Cut Line= 4
      1453538.59      6891685.99      1453685.48      6891431.39
      1455219.35      6888773.12      1457109.66      6885725.80
#Sta/Elev= 30
  1637.0 1851.76  1731.6 1851.73  2067.9 1849.21  2220.3 1845.73  2271.6 1843.49
  2389.2 1845.12  4479.2 1849.19  4728.8 1850.19  4877.2 1840.89  4963.4 1842.97
  4992.7 1829.70  4992.8 1827.70  5008.7 1829.70  5021.9 1834.73  5029.6 1843.74
  5088.6 1846.83  5262.9 1844.59  5299.5 1835.29  5370.8 1851.30  5829.8 1849.54
  5887.8 1842.46  6053.3 1842.26  6161.8 1847.62  7986.6 1861.20  7999.4 1861.36
  8161.7 1863.55  8195.2 1863.95  8429.2 1866.27  8486.9 1866.80  8586.0 1867.46
#Mann=16,-1,0
  1637.0   0.035       0  1731.6   0.045       0  2067.9    0.07       0
  2220.3   0.035       0  2271.6    0.07       0  2389.2   0.045       0
  4479.2   0.035       0  4992.7   0.035       0  5008.7    0.07       0
  5088.6    0.07       0  7986.6   0.035       0  7999.4    0.07       0
  8161.7   0.035       0  8195.2    0.07       0  8429.2   0.035       0
  8486.9    0.07       0
Bank Sta=4992.7,5008.7
Exp/Cntr=0.3,0.1

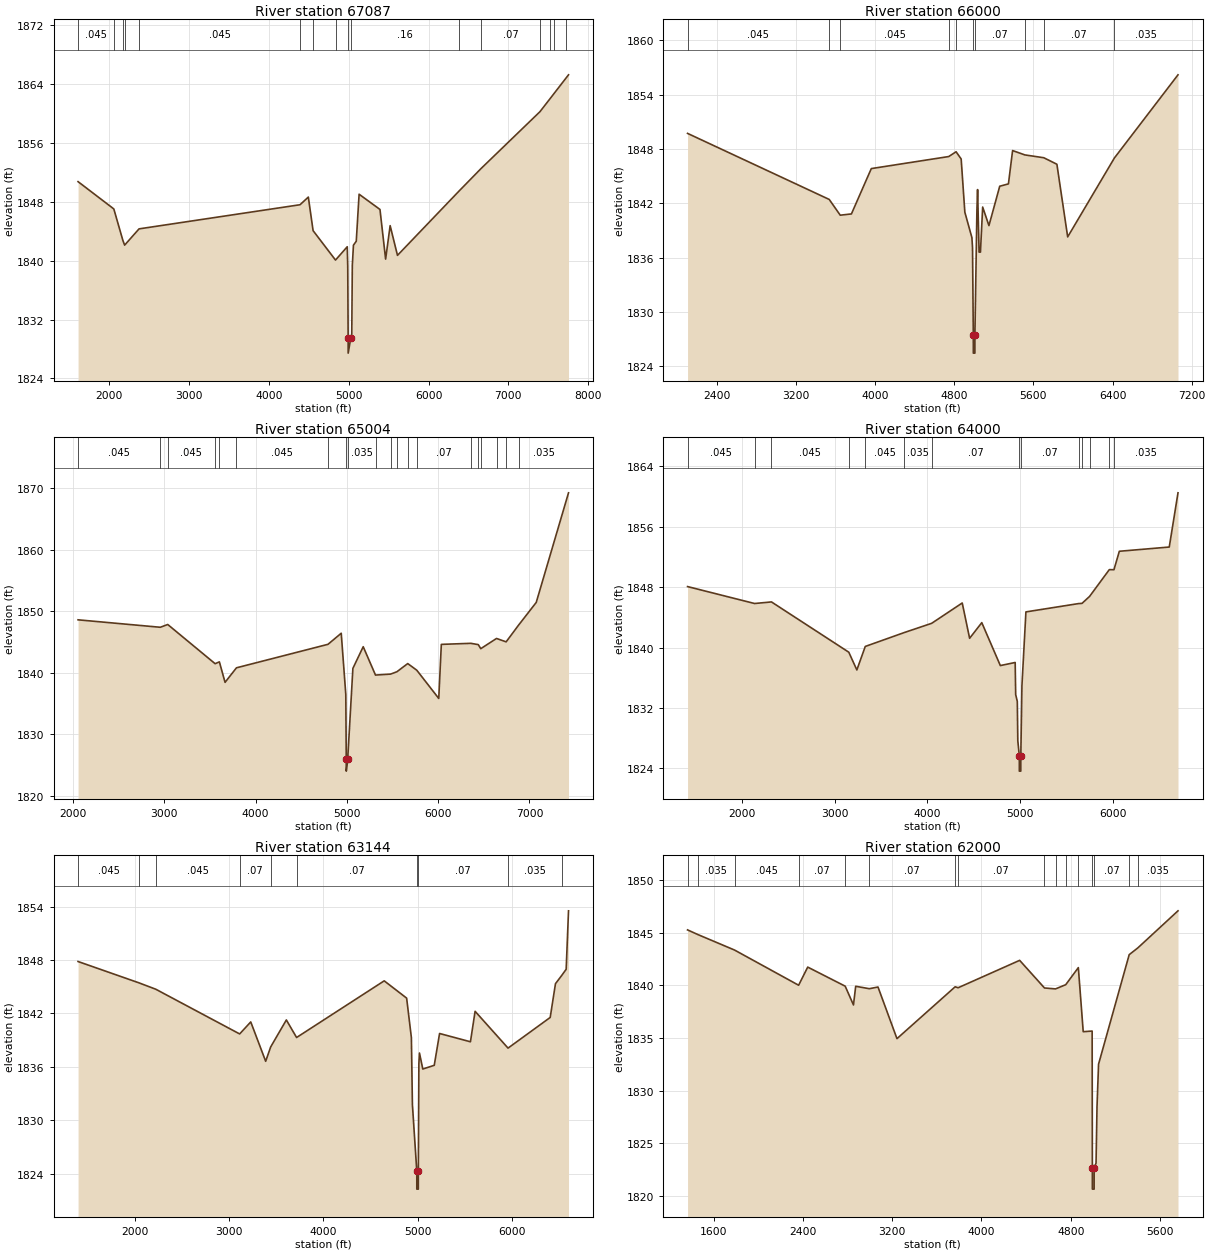
Type RM Length L Ch R = 1,67087,1087,1087,1087
BEGIN DESCRIPTION:
Sweetwater Creek 133.0
END DESCRIPTION:
XS GIS Cut Line= 4
      1453963.04      6891726.71      1454092.06      6891549.59
      1455959.47      6888986.32      1457905.02      6887037.98
#Sta/Elev= 30
  1609.5 1850.75  2057.4 1847.04  2170.4 1842.78  2192.8 1842.12  2373.5 1844.33
  4389.9 1847.61  4494.1 1848.65  4553.7 1844.09  4834.5 1840.09  4981.6 1841.90
  4987.8 1839.27  4992.9 1829.44  4993.2 1827.44  5025.0 1829.44  5038.1 1830.03
  5045.1 1839.36  5059.3 1842.12  5094.6 1842.65  5130.0 1849.04  5391.6 1846.97
  5462.3 1840.22  5518.9 1844.77  5610.8 1840.73  6382.8 1849.48  6658.6 1852.54
  7395.7 1860.26  7517.4 1861.96  7570.8 1862.71  7720.5 1864.81  7753.4 1865.27
#Mann=16,-1,0
  1609.5   0.045       0  2057.4    0.07       0  2170.4   0.045       0
  2192.8    0.07       0  2373.5   0.045       0  4389.9   0.035       0
  4553.7    0.07       0  4834.5    0.16       0  4992.9    0.07       0
  5025.0    0.16       0  6382.8   0.035       0  6658.6    0.07       0
  7395.7   0.035       0  7517.4    0.07       0  7570.8   0.035       0
  7720.5    0.07       0
Bank Sta=4992.9,5025
Exp/Cntr=0.3,0.1

Type RM Length L Ch R = 1,66000,996,996,996
BEGIN DESCRIPTION:
Sweetwater Creek 131.0
END DESCRIPTION:
XS GIS Cut Line= 4
      1454236.49      6891973.93      1454812.43      6891482.74
      1456070.73      6889752.69      1457804.99      6888638.01
#Sta/Elev= 30
  2103.8 1849.73  3536.1 1842.43  3647.3 1840.69  3760.4 1840.83  3961.3 1845.84
  4743.7 1847.17  4818.4 1847.70  4869.8 1846.90  4906.9 1841.02  4978.3 1838.21
  4984.5 1837.10  4992.5 1827.45  4992.7 1825.45  5008.4 1825.45  5008.6 1827.45
  5028.9 1841.28  5035.6 1843.52  5050.8 1836.61  5064.5 1836.61  5087.1 1841.59
  5150.5 1839.54  5259.5 1843.89  5347.4 1844.15  5389.6 1847.83  5514.1 1847.35
  5704.7 1847.04  5837.4 1846.32  5946.4 1838.29  6418.6 1847.01  7061.6 1856.20
#Mann=10,-1,0
  2103.8   0.045       0  3536.1    0.07       0  3647.3   0.045       0
  4743.7   0.035       0  4818.4    0.07       0  4992.5    0.07       0
  5008.6    0.07       0  5514.1   0.035       0  5704.7    0.07       0
  6418.6   0.035       0
Bank Sta=4992.5,5008.6
Exp/Cntr=0.3,0.1

Type RM Length L Ch R = 1,65004,1004,1004,1004
BEGIN DESCRIPTION:
Sweetwater Creek 129.0
END DESCRIPTION:
XS GIS Cut Line= 4
      1454332.84      6892028.62      1455325.08      6891462.46
      1456773.32      6890385.78      1458503.26      6888686.27
#Sta/Elev= 30
  2055.3 1848.62  2955.6 1847.41  3037.6 1847.86  3556.6 1841.49  3603.2 1841.79
  3665.5 1838.46  3790.1 1840.82  4793.0 1844.64  4937.9 1846.44  4988.0 1836.48
  4992.9 1826.03  4993.0 1824.03  5008.9 1826.03  5065.6 1840.73  5178.7 1844.25
  5313.3 1839.64  5478.7 1839.80  5547.5 1840.18  5666.4 1841.51  5765.5 1840.43
  6006.1 1835.84  6034.3 1844.63  6357.2 1844.80  6439.0 1844.59  6466.1 1843.93
  6638.8 1845.59  6744.2 1845.04  6880.1 1847.75  7073.9 1851.45  7427.4 1869.26
#Mann=20,-1,0
  2055.3   0.045       0  2955.6   0.035       0  3037.6   0.045       0
  3556.6    0.07       0  3603.2   0.045       0  3790.1   0.045       0
  4793.0   0.035       0  4992.9   0.035       0  5008.9   0.035       0
  5313.3    0.07       0  5478.7   0.035       0  5547.5    0.07       0
  5666.4   0.035       0  5765.5    0.07       0  6357.2   0.035       0
  6439.0    0.07       0  6466.1   0.035       0  6638.8    0.07       0
  6744.2    0.07       0  6880.1   0.035       0
Bank Sta=4992.9,5008.9
Exp/Cntr=0.3,0.1

Type RM Length L Ch R = 1,64000,856,856,856
BEGIN DESCRIPTION:
Sweetwater Creek 127.0
END DESCRIPTION:
XS GIS Cut Line= 4
      1454426.63      6892078.08      1455462.28      6891591.91
      1457679.91      6890561.54      1458773.39      6889254.02
#Sta/Elev= 30
  1410.6 1848.06  2134.1 1845.82  2316.4 1846.03  3151.0 1839.38  3238.1 1837.03
  3328.8 1840.14  3750.1 1841.98  4045.6 1843.20  4375.5 1845.89  4455.2 1841.22
  4586.6 1843.29  4786.8 1837.61  4947.0 1838.02  4952.5 1833.77  4969.9 1832.87
  4975.4 1827.68  4991.8 1825.65  4991.9 1823.65  5007.7 1823.65  5007.9 1825.65
  5019.9 1834.94  5062.9 1844.71  5631.2 1845.81  5668.5 1845.84  5750.2 1846.76
  5963.0 1850.30  6013.1 1850.29  6071.4 1852.73  6610.1 1853.29  6704.5 1860.46
#Mann=14,-1,0
  1410.6   0.045       0  2134.1   0.035       0  2316.4   0.045       0
  3151.0    0.07       0  3328.8   0.045       0  3750.1   0.035       0
  4045.6    0.07       0  4991.8    0.07       0  5007.9    0.07       0
  5631.2   0.035       0  5668.5    0.07       0  5750.2   0.035       0
  5963.0    0.07       0  6013.1   0.035       0
Bank Sta=4991.8,5007.9
Exp/Cntr=0.3,0.1

Type RM Length L Ch R = 1,63144,1144,1144,1144
BEGIN DESCRIPTION:
Sweetwater Creek 125.0
END DESCRIPTION:
XS GIS Cut Line= 4
      1454465.72      6892130.15      1455224.96      6891814.27
      1457949.03      6891240.34      1458948.66      6889987.46
#Sta/Elev= 30
  1393.8 1847.83  2039.5 1845.44  2219.1 1844.72  3110.0 1839.70  3227.9 1841.05
  3386.4 1836.63  3439.5 1838.24  3606.0 1841.27  3714.7 1839.30  4645.4 1845.66
  4883.5 1843.72  4934.0 1839.28  4944.8 1831.78  4991.5 1824.28  4991.6 1822.28
  5007.4 1822.28  5007.6 1824.28  5013.5 1836.35  5019.9 1837.56  5055.1 1835.76
  5176.8 1836.18  5233.3 1839.75  5561.1 1838.82  5610.7 1842.24  5960.5 1838.11
  6408.2 1841.55  6464.2 1845.34  6533.0 1846.30  6577.9 1846.96  6602.8 1853.52
#Mann=10,-1,0
  1393.8   0.045       0  2039.5   0.035       0  2219.1   0.045       0
  3110.0    0.07       0  3439.5   0.035       0  3714.7    0.07       0
  4991.5    0.07       0  5007.6    0.07       0  5960.5   0.035       0
  6533.0    0.07       0
Bank Sta=4991.5,5007.6
Exp/Cntr=0.3,0.1

Type RM Length L Ch R = 1,62000,1000,1000,1000
BEGIN DESCRIPTION:
Sweetwater Creek 122.0
END DESCRIPTION:
XS GIS Cut Line= 3
      1454927.37      6892111.64      1458562.73      6892043.41
      1459249.77      6891713.38
#Sta/Elev= 30
  1364.0 1845.26  1458.4 1844.81  1785.1 1843.35  2360.1 1840.01  2441.8 1841.73
  2777.6 1839.92  2851.9 1838.14  2871.9 1839.91  2994.0 1839.68  3071.9 1839.84
  3242.0 1834.94  3763.7 1839.86  3790.4 1839.77  4342.2 1842.37  4564.8 1839.75
  4663.9 1839.66  4755.4 1840.06  4868.5 1841.68  4912.3 1835.60  4992.3 1835.66
  4994.1 1822.66  4994.3 1820.66  5010.1 1820.66  5010.2 1822.66  5027.2 1823.13
  5035.8 1828.46  5049.8 1832.52  5324.6 1842.91  5401.8 1843.55  5762.2 1847.07
#Mann=16,-1,0
  1364.0   0.045       0  1458.4   0.035       0  1785.1   0.045       0
  2360.1    0.07       0  2777.6   0.035       0  2994.0    0.07       0
  3763.7   0.035       0  3790.4    0.07       0  4564.8   0.035       0
  4663.9    0.07       0  4755.4   0.035       0  4868.5    0.07       0
  4994.1    0.07       0  5010.2    0.07       0  5324.6    0.07       0
  5401.8   0.035       0
Bank Sta=4994.1,5010.2
Exp/Cntr=0.3,0.1

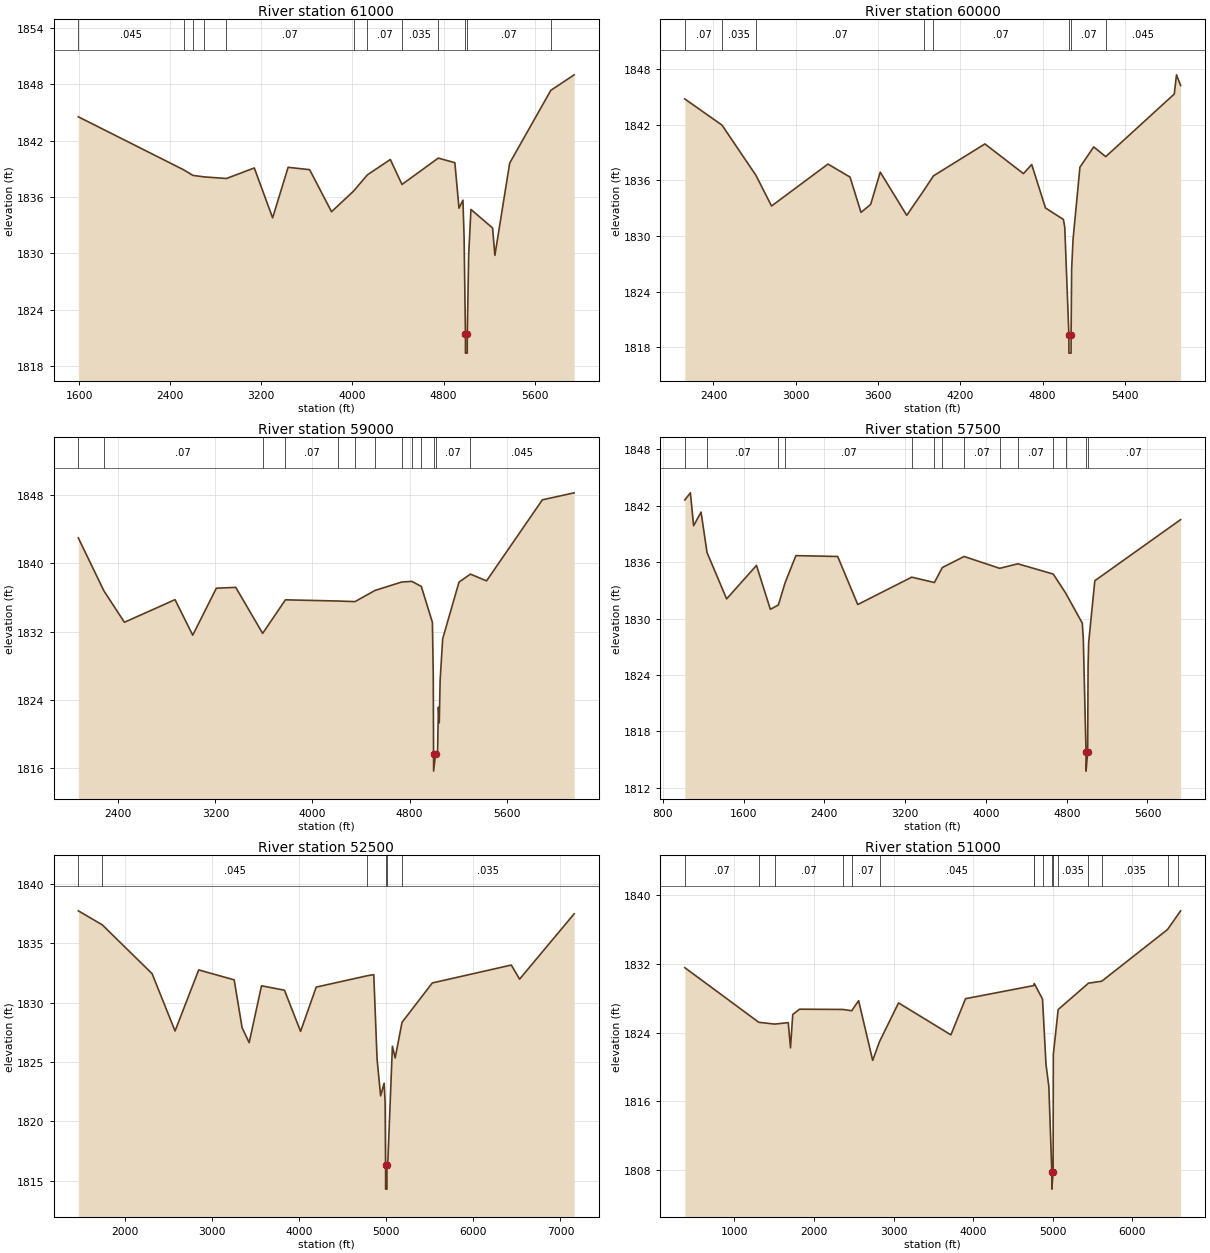
Type RM Length L Ch R = 1,61000,1000,1000,1000
BEGIN DESCRIPTION:
Sweetwater Creek 121.0
END DESCRIPTION:
XS GIS Cut Line= 3
      1455138.55      6892421.24      1458504.99      6892942.82
      1459450.74      6892921.06
#Sta/Elev= 30
  1593.4 1844.53  2517.1 1838.90  2599.2 1838.30  2698.9 1838.14  2893.3 1837.97
  3138.1 1839.09  3299.0 1833.79  3435.1 1839.16  3623.8 1838.91  3816.1 1834.44
  4010.5 1836.64  4130.0 1838.35  4332.1 1839.99  4434.7 1837.34  4753.4 1840.14
  4898.8 1839.65  4935.0 1834.82  4969.7 1835.67  4979.8 1831.75  4991.7 1821.41
  4991.8 1819.41  5007.7 1819.41  5007.8 1821.41  5020.0 1829.86  5040.0 1834.68
  5230.1 1832.71  5250.1 1829.80  5380.1 1839.61  5741.1 1847.34  5946.0 1848.99
#Mann=12,-1,0
  1593.4   0.045       0  2517.1    0.07       0  2599.2   0.045       0
  2698.9   0.035       0  2893.3    0.07       0  4010.5   0.035       0
  4130.0    0.07       0  4434.7   0.035       0  4753.4    0.07       0
  4991.7    0.07       0  5007.8    0.07       0  5741.1   0.045       0
Bank Sta=4991.7,5007.8
Exp/Cntr=0.3,0.1

Type RM Length L Ch R = 1,60000,1000,1000,1000
BEGIN DESCRIPTION:
Sweetwater Creek 119.0
END DESCRIPTION:
XS GIS Cut Line= 3
      1455654.96      6893588.00      1458453.93      6893822.79
      1459254.95      6893738.01
#Sta/Elev= 30
  2191.2 1844.76  2462.5 1841.94  2710.0 1836.52  2823.5 1833.22  3234.9 1837.74
  3395.5 1836.34  3475.7 1832.53  3546.0 1833.39  3616.2 1836.87  3809.1 1832.21
  3934.6 1834.92  4003.9 1836.47  4378.9 1839.91  4659.9 1836.71  4720.1 1837.69
  4820.4 1833.01  4950.9 1831.77  4960.9 1830.94  4991.0 1819.36  4991.2 1817.36
  5007.0 1817.36  5007.2 1819.36  5011.1 1826.41  5021.2 1829.61  5071.5 1837.40
  5172.0 1839.59  5259.6 1838.54  5759.2 1845.29  5775.4 1847.36  5805.5 1846.21
#Mann=8,-1,0
  2191.2    0.07       0  2462.5   0.035       0  2710.0    0.07       0
  3934.6   0.035       0  4003.9    0.07       0  4991.0    0.07       0
  5007.2    0.07       0  5259.6   0.045       0
Bank Sta=4991,5007.2
Exp/Cntr=0.3,0.1

Type RM Length L Ch R = 1,59000,1500,1500,1500
BEGIN DESCRIPTION:
Sweetwater Creek 117.0
END DESCRIPTION:
XS GIS Cut Line= 4
      1455910.77      6893812.51      1458525.45      6894579.40
      1458672.72      6894438.26      1459455.01      6893587.99
#Sta/Elev= 30
  2071.2 1842.98  2281.1 1836.80  2450.8 1833.10  2867.6 1835.75  3013.5 1831.59
  3208.1 1837.09  3367.8 1837.19  3589.5 1831.80  3777.0 1835.73  4208.2 1835.59
  4350.2 1835.52  4515.2 1836.83  4734.0 1837.81  4818.2 1837.89  4896.3 1837.30
  4987.8 1833.09  4994.7 1827.00  4997.4 1817.67  4997.6 1815.67  5013.6 1817.67
  5029.9 1817.67  5037.3 1823.16  5044.1 1821.32  5051.5 1826.34  5072.5 1831.17
  5206.9 1837.80  5300.5 1838.74  5433.7 1837.95  5893.7 1847.44  6155.4 1848.26
#Mann=13,-1,0
  2071.2   0.035       0  2281.1    0.07       0  3589.5   0.035       0
  3777.0    0.07       0  4208.2   0.035       0  4350.2    0.07       0
  4515.2   0.035       0  4734.0    0.07       0  4818.2   0.035       0
  4896.3    0.07       0  4997.4    0.07       0  5013.6    0.07       0
  5300.5   0.045       0
Bank Sta=4997.4,5013.6
Exp/Cntr=0.3,0.1

Type RM Length L Ch R = 1,57500,5000,5000,5000
BEGIN DESCRIPTION:
Sweetwater Creek 114.0
END DESCRIPTION:
XS GIS Cut Line= 5
      1455802.37      6894208.53      1458931.84      6895267.98
      1459610.48      6895288.87      1459762.34      6895211.55
      1460435.64      6894863.39
#Sta/Elev= 30
  1017.1 1842.61  1072.7 1843.37  1104.3 1839.87  1178.2 1841.32  1237.3 1837.02
  1431.4 1832.09  1727.2 1835.65  1864.5 1830.98  1943.9 1831.44  2009.8 1833.78
  2117.5 1836.69  2531.4 1836.60  2730.2 1831.49  3265.0 1834.40  3489.7 1833.83
  3567.7 1835.42  3784.0 1836.60  4136.1 1835.34  4316.2 1835.82  4666.8 1834.73
  4788.3 1832.73  4954.5 1829.51  4964.5 1827.82  4991.4 1815.77  4991.5 1813.77
  5007.6 1815.77  5011.8 1824.98  5017.4 1827.42  5078.5 1834.02  5928.4 1840.52
#Mann=14,-1,0
  1017.1   0.035       0  1237.3    0.07       0  1943.9   0.035       0
  2009.8    0.07       0  3265.0   0.035       0  3489.7    0.07       0
  3567.7   0.035       0  3784.0    0.07       0  4136.1   0.035       0
  4316.2    0.07       0  4666.8   0.035       0  4788.3    0.07       0
  4991.4    0.07       0  5007.6    0.07       0
Bank Sta=4991.4,5007.6
Exp/Cntr=0.3,0.1

Type RM Length L Ch R = 1,52500,1500,1500,1500
BEGIN DESCRIPTION:
Sweetwater Creek 104.0
END DESCRIPTION:
XS GIS Cut Line= 5
      1455318.68      6895998.66      1458807.41      6896545.33
      1459326.64      6896735.12      1459678.15      6896734.27
      1460771.02      6896121.47
#Sta/Elev= 30
  1468.7 1837.74  1743.2 1836.56  2315.2 1832.44  2578.4 1827.61  2849.9 1832.76
  3256.6 1831.92  3347.7 1827.89  3428.7 1826.63  3570.4 1831.42  3833.5 1831.05
  4018.4 1827.58  4197.9 1831.31  4784.7 1832.27  4858.3 1832.36  4896.3 1825.22
  4936.8 1822.14  4977.3 1823.21  4988.7 1821.56  4993.7 1816.28  4993.8 1814.28
  5009.7 1814.28  5009.9 1816.28  5017.9 1816.28  5072.0 1826.32  5103.9 1825.34
  5182.4 1828.34  5529.8 1831.66  6436.2 1833.17  6531.3 1831.98  7157.3 1837.49
#Mann=6,-1,0
  1468.7   0.035       0  1743.2   0.045       0  4784.7    0.07       0
  4993.7    0.07       0  5009.9    0.07       0  5182.4   0.035       0
Bank Sta=4993.7,5009.9
Exp/Cntr=0.3,0.1

Type RM Length L Ch R = 1,51000,1000,1000,1000
BEGIN DESCRIPTION:
Sweetwater Creek 101.0
END DESCRIPTION:
XS GIS Cut Line= 3
      1456353.73      6900624.89      1459623.28      6897356.11
      1460904.96      6896388.03
#Sta/Elev= 30
   376.7 1831.53  1306.2 1825.19  1506.7 1824.98  1676.5 1825.15  1704.8 1822.22
  1733.0 1826.09  1817.9 1826.71  2362.9 1826.68  2473.8 1826.53  2560.4 1827.70
  2737.1 1820.77  2823.5 1822.95  3062.4 1827.44  3720.0 1823.73  3903.9 1827.93
  4760.5 1829.45  4767.2 1829.69  4871.0 1827.89  4915.0 1820.28  4950.4 1817.76
  4988.0 1807.82  4988.1 1805.82  5004.2 1807.82  5006.8 1821.45  5067.9 1826.67
  5448.3 1829.73  5615.8 1829.96  6441.7 1835.96  6568.5 1837.63  6606.2 1838.13
#Mann=16,-1,0
   376.7    0.07       0  1306.2   0.035       0  1506.7    0.07       0
  2362.9   0.035       0  2473.8    0.07       0  2823.5   0.045       0
  4760.5    0.07       0  4767.2   0.045       0  4871.0    0.07       0
  4988.0    0.07       0  5004.2    0.07       0  5067.9   0.035       0
  5448.3    0.07       0  5615.8   0.035       0  6441.7    0.07       0
  6568.5   0.035       0
Bank Sta=4988,5004.2
Exp/Cntr=0.3,0.1

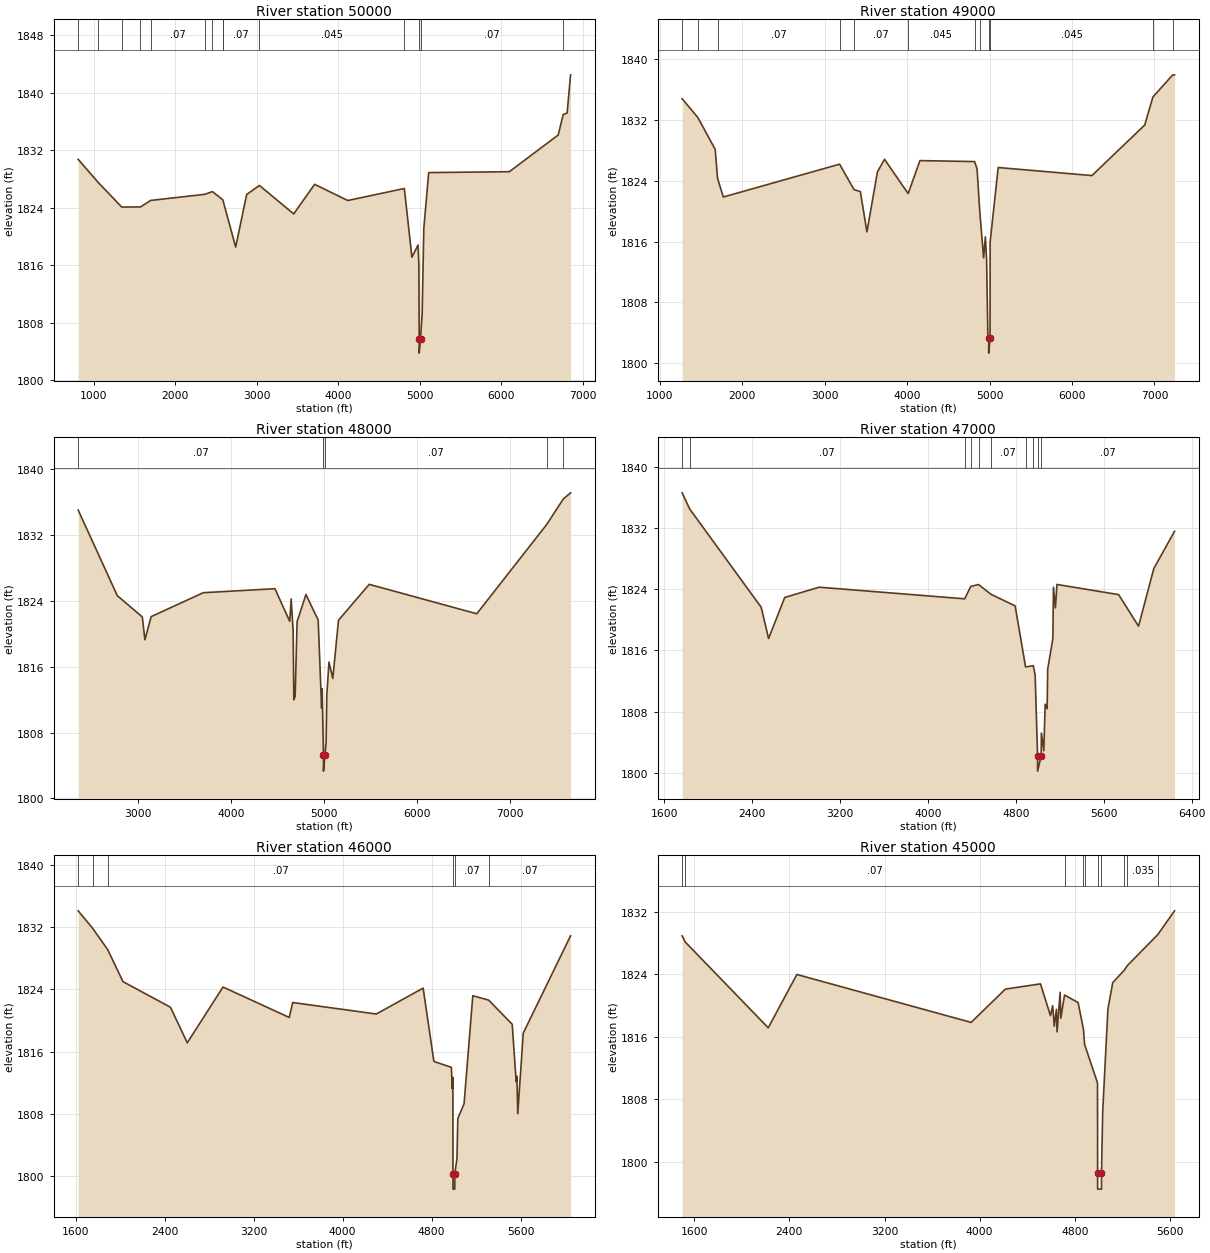
Type RM Length L Ch R = 1,50000,1000,1000,1000
BEGIN DESCRIPTION:
Sweetwater Creek 99.0
END DESCRIPTION:
XS GIS Cut Line= 4
      1456808.81      6900433.71      1460024.78      6897959.77
      1460155.43      6898000.52      1462007.12      6897998.87
#Sta/Elev= 30
   805.7 1830.72  1049.5 1827.54  1340.9 1824.09  1570.8 1824.11  1695.9 1825.01
  2359.8 1825.86  2454.4 1826.24  2579.7 1825.12  2582.1 1825.09  2739.8 1818.53
  2874.8 1825.84  3031.7 1827.09  3452.0 1823.14  3709.4 1827.25  4116.3 1825.00
  4810.6 1826.67  4903.8 1817.12  4979.3 1818.82  4989.1 1816.12  4992.9 1805.80
  4993.0 1803.80  5009.1 1805.80  5029.6 1809.28  5049.6 1821.10  5109.6 1828.88
  6099.6 1829.00  6699.6 1834.10  6761.9 1836.96  6809.6 1837.15  6851.7 1842.46
#Mann=14,-1,0
   805.7    0.07       0  1049.5   0.035       0  1340.9    0.07       0
  1570.8   0.035       0  1695.9    0.07       0  2359.8   0.045       0
  2454.4   0.035       0  2579.7   0.045       0  2582.1    0.07       0
  3031.7   0.045       0  4810.6    0.07       0  4992.9    0.07       0
  5009.1    0.07       0  6761.9   0.035       0
Bank Sta=4992.9,5009.1
Exp/Cntr=0.3,0.1

Type RM Length L Ch R = 1,49000,1000,1000,1000
BEGIN DESCRIPTION:
Sweetwater Creek 97.0
END DESCRIPTION:
XS GIS Cut Line= 5
      1456840.53      6900671.65      1459578.34      6898687.23
      1459872.08      6898870.53      1460203.04      6899051.89
      1462020.58      6898631.14
#Sta/Elev= 30
  1272.4 1834.79  1462.2 1832.33  1673.0 1828.14  1702.3 1824.30  1771.9 1821.86
  3181.9 1826.18  3355.5 1822.85  3433.6 1822.57  3513.3 1817.28  3640.8 1825.17
  3726.6 1826.82  4013.3 1822.31  4155.8 1826.65  4818.9 1826.52  4848.9 1825.55
  4880.8 1820.03  4928.0 1813.86  4949.2 1816.62  4964.5 1813.57  4979.9 1803.33
  4989.9 1803.33  4990.0 1801.33  5006.1 1803.33  5007.1 1815.94  5104.7 1825.74
  6241.6 1824.68  6881.6 1831.33  6980.6 1835.01  7221.6 1837.93  7243.0 1837.91
#Mann=12,-1,0
  1272.4    0.07       0  1462.2   0.035       0  1702.3    0.07       0
  3181.9   0.035       0  3355.5    0.07       0  4013.3   0.045       0
  4818.9    0.07       0  4880.8   0.045       0  4989.9    0.07       0
  5006.1   0.045       0  6980.6   0.035       0  7221.6    0.07       0
Bank Sta=4989.9,5006.1
Exp/Cntr=0.3,0.1

Type RM Length L Ch R = 1,48000,1000,1000,1000
BEGIN DESCRIPTION:
Sweetwater Creek 95.0
END DESCRIPTION:
XS GIS Cut Line= 4
      1457110.86      6900991.64      1459373.83      6899619.43
      1459671.86      6899555.25      1461923.21      6898892.62
#Sta/Elev= 30
  2353.5 1835.07  2774.3 1824.66  3043.8 1822.06  3071.7 1819.29  3138.8 1822.10
  3699.2 1825.01  4470.8 1825.50  4629.8 1821.53  4645.3 1824.26  4666.7 1820.29
  4673.9 1811.99  4688.0 1812.39  4709.3 1821.49  4804.3 1824.79  4936.2 1821.68
  4973.0 1810.97  4978.8 1813.32  4993.0 1805.31  4993.2 1803.31  5009.3 1805.31
  5021.7 1806.89  5028.7 1812.56  5052.3 1816.57  5093.3 1814.57  5154.6 1821.66
  5485.0 1826.03  6642.4 1822.45  7395.1 1833.31  7572.7 1836.40  7651.7 1837.16
#Mann=5,-1,0
  2353.5    0.07       0  4993.0    0.07       0  5009.3    0.07       0
  7395.1   0.035       0  7572.7    0.07       0
Bank Sta=4993,5009.3
Exp/Cntr=0.3,0.1

Type RM Length L Ch R = 1,47000,1000,1000,1000
BEGIN DESCRIPTION:
Sweetwater Creek 93.0
END DESCRIPTION:
XS GIS Cut Line= 4
      1457274.37      6901486.90      1460032.63      6900073.95
      1460065.56      6899937.98      1461204.99      6899438.00
#Sta/Elev= 30
  1761.0 1836.60  1830.7 1834.47  2480.8 1821.64  2548.2 1817.55  2695.3 1822.92
  3008.9 1824.26  4333.8 1822.74  4388.8 1824.36  4459.7 1824.61  4572.6 1823.34
  4793.1 1821.81  4888.1 1813.83  4958.4 1814.00  4975.3 1812.76  4997.4 1802.21
  4997.7 1800.21  5029.9 1802.21  5032.0 1805.19  5054.0 1802.87  5066.3 1808.97
  5084.2 1808.37  5089.6 1813.55  5136.4 1817.54  5141.8 1824.26  5159.7 1821.56
  5174.1 1824.62  5735.3 1823.29  5916.7 1819.16  6055.4 1826.69  6244.3 1831.57
#Mann=10,-1,0
  1761.0   0.035       0  1830.7    0.07       0  4333.8    0.16       0
  4388.8    0.07       0  4459.7    0.16       0  4572.6    0.07       0
  4888.1    0.16       0  4958.4    0.07       0  4997.4    0.07       0
  5029.9    0.07       0
Bank Sta=4997.4,5029.9
Exp/Cntr=0.3,0.1

Type RM Length L Ch R = 1,46000,1000,1000,1000
BEGIN DESCRIPTION:
Sweetwater Creek 91.0
END DESCRIPTION:
XS GIS Cut Line= 3
      1457346.68      6902005.22      1460404.68      6900568.23
      1461204.97      6899888.03
#Sta/Elev= 30
  1621.2 1834.10  1751.3 1831.86  1887.5 1829.10  2024.4 1825.00  2451.5 1821.71
  2602.7 1817.14  2924.1 1824.31  3519.8 1820.40  3550.9 1822.32  4302.8 1820.84
  4724.1 1824.17  4821.1 1814.75  4978.3 1813.98  4986.3 1811.23  4991.8 1812.68
  4992.6 1800.34  4992.8 1798.34  5008.7 1798.34  5008.9 1800.34  5028.4 1802.23
  5036.1 1807.43  5092.3 1809.30  5171.0 1823.19  5313.4 1822.63  5525.4 1819.52
  5561.1 1812.14  5567.6 1812.85  5575.4 1808.04  5624.8 1818.39  6050.3 1830.89
#Mann=6,-1,0
  1621.2    0.07       0  1751.3   0.035       0  1887.5    0.07       0
  4992.6    0.07       0  5008.9    0.07       0  5313.4    0.07       0
Bank Sta=4992.6,5008.9
Exp/Cntr=0.3,0.1

Type RM Length L Ch R = 1,45000,1000,1000,1000
BEGIN DESCRIPTION:
Sweetwater Creek 89.0
END DESCRIPTION:
XS GIS Cut Line= 3
      1457610.89      6901984.42      1460927.68      6900859.99
      1461555.02      6900738.00
#Sta/Elev= 30
  1497.8 1828.89  1524.3 1828.10  2222.0 1817.13  2462.7 1823.95  3928.5 1817.82
  4216.5 1822.08  4511.5 1822.75  4595.9 1818.68  4614.3 1819.95  4627.6 1817.35
  4645.7 1819.50  4651.0 1816.61  4677.1 1821.68  4682.4 1818.35  4714.0 1821.32
  4828.2 1820.36  4873.3 1816.91  4882.6 1815.02  4991.3 1810.08  4992.2 1798.50
  4992.5 1796.50  5024.5 1796.50  5024.8 1798.50  5034.8 1806.37  5078.8 1819.52
  5119.5 1822.91  5214.9 1824.47  5242.7 1825.09  5498.7 1829.06  5639.1 1832.09
#Mann=10,-1,0
  1497.8   0.035       0  1524.3    0.07       0  4714.0    0.16       0
  4873.3    0.07       0  4882.6    0.16       0  4992.2    0.07       0
  5024.8    0.16       0  5214.9    0.07       0  5242.7   0.035       0
  5498.7    0.07       0
Bank Sta=4992.2,5024.8
Exp/Cntr=0.3,0.1