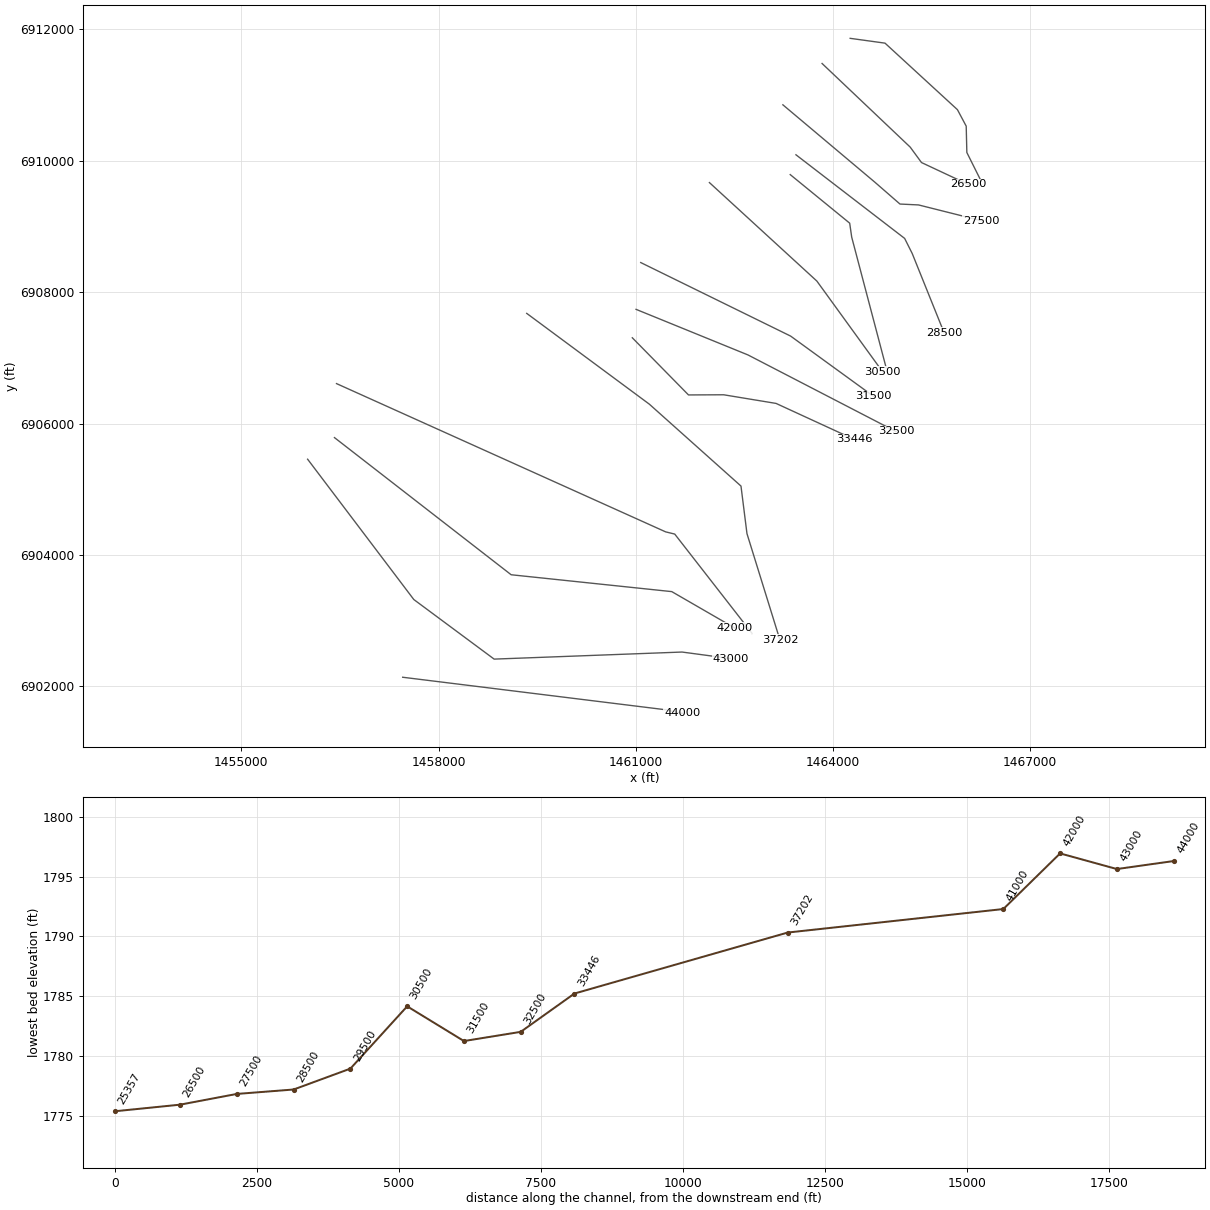
HEC-RAS study Sweetwater Creek.prj: Sweetwater Creek Base Level Engineering

--- Sweetwater Creek.g01 (geometry) --- (continued)

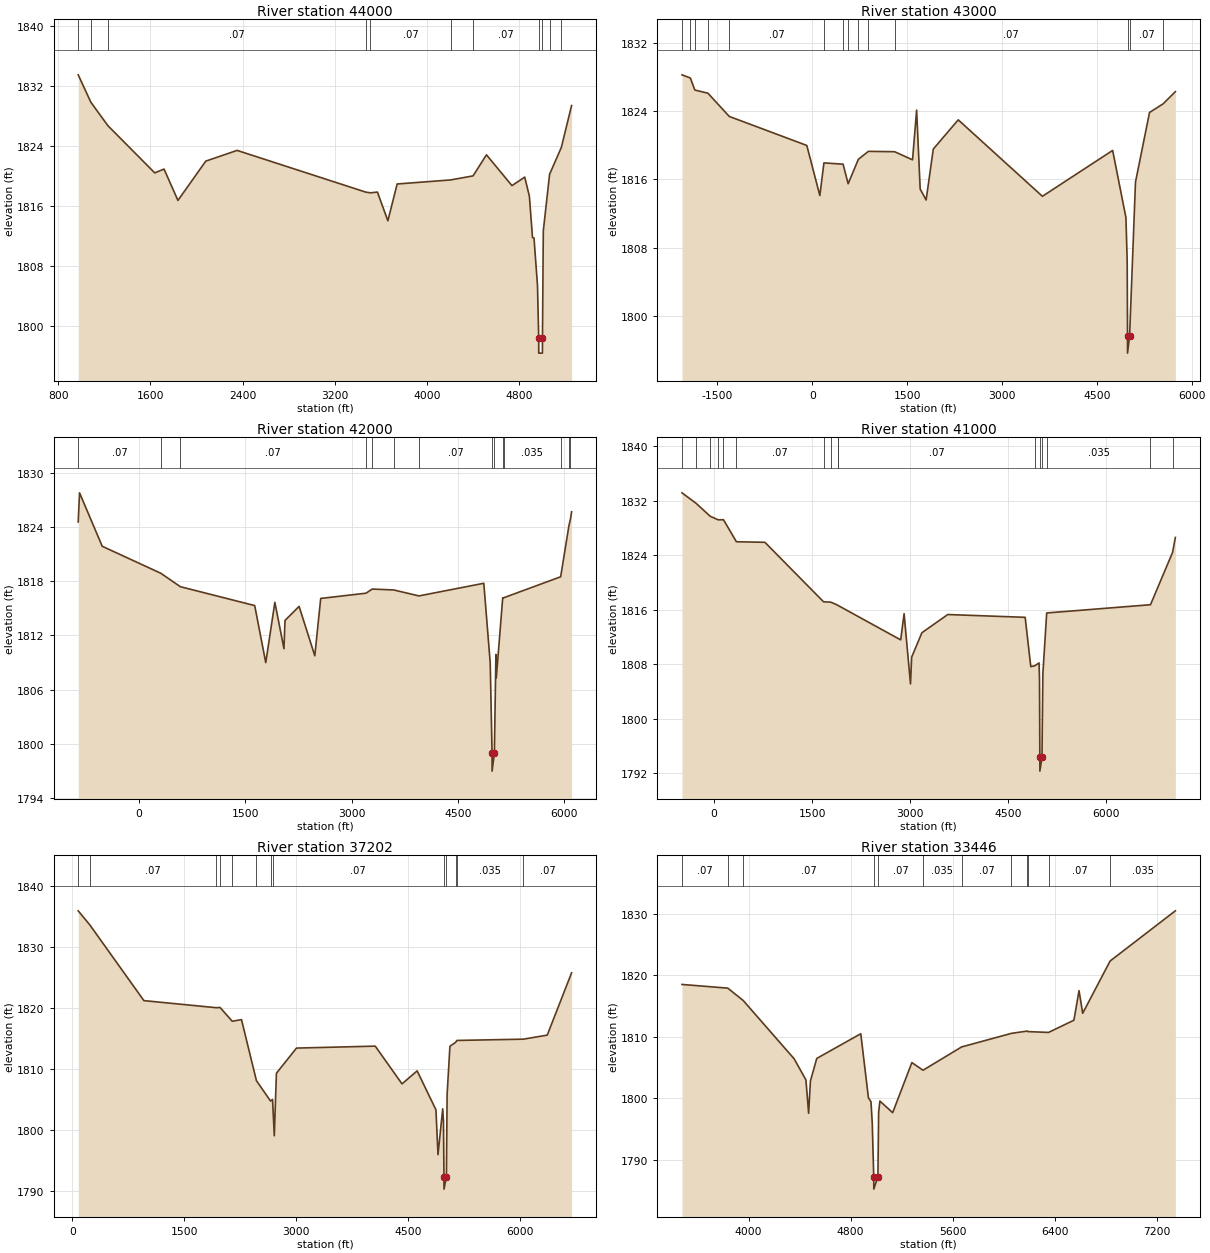
Type RM Length L Ch R = 1,44000,1000,1000,1000
BEGIN DESCRIPTION:
Sweetwater Creek 87.0
END DESCRIPTION:
XS GIS Cut Line= 3
      1457455.01      6902138.00      1461452.22      6901643.34
      1461705.04      6901587.99
#Sta/Elev= 30
   972.3 1833.44  1082.4 1829.78  1230.2 1826.66  1637.3 1820.36  1717.9 1820.87
  1838.8 1816.69  2080.7 1821.93  2352.7 1823.36  3469.8 1817.80  3511.3 1817.70
  3572.0 1817.80  3662.7 1813.97  3743.3 1818.88  4207.3 1819.42  4402.6 1819.96
  4519.2 1822.77  4740.8 1818.66  4851.7 1819.80  4892.0 1817.26  4919.2 1811.73
  4932.3 1811.68  4962.5 1805.36  4973.2 1798.32  4973.5 1796.32  5005.5 1796.32
  5005.8 1798.32  5013.1 1812.63  5067.8 1820.18  5169.8 1823.76  5258.8 1829.34
#Mann=11,-1,0
   972.3    0.07       0  1082.4   0.035       0  1230.2    0.07       0
  3469.8   0.035       0  3511.3    0.07       0  4207.3   0.035       0
  4402.6    0.07       0  4973.2    0.07       0  5005.8    0.07       0
  5067.8   0.035       0  5169.8    0.07       0
Bank Sta=4973.2,5005.8
Exp/Cntr=0.3,0.1

Type RM Length L Ch R = 1,43000,1000,1000,1000
BEGIN DESCRIPTION:
Sweetwater Creek 85.0
END DESCRIPTION:
XS GIS Cut Line= 6
      1456008.85      6905456.93      1457624.02      6903321.10
      1458846.09      6902414.03      1461704.16      6902521.62
      1461955.00      6902488.00      1462439.98      6902423.00
#Sta/Elev= 30
 -2059.8 1828.23 -1927.4 1827.86 -1856.8 1826.45 -1649.8 1826.08 -1312.1 1823.36
   -85.7 1819.96   120.4 1814.10   184.8 1817.92   488.0 1817.77   567.9 1815.48
   730.3 1818.35   888.7 1819.27  1302.2 1819.23  1586.2 1818.28  1650.8 1824.10
  1707.1 1814.86  1801.1 1813.58  1914.4 1819.54  2308.9 1822.96  3639.9 1814.01
  4750.7 1819.38  4960.8 1811.52  4980.8 1806.35  4985.9 1797.65  4986.2 1795.65
  5018.5 1797.65  5111.8 1815.67  5333.8 1823.82  5549.7 1824.84  5742.4 1826.26
#Mann=14,-1,0
 -2059.8    0.07       0 -1927.4   0.035       0 -1856.8    0.07       0
 -1649.8   0.035       0 -1312.1    0.07       0   184.8    0.16       0
   488.0    0.07       0   567.9    0.16       0   730.3    0.07       0
   888.7   0.035       0  1302.2    0.07       0  4985.9    0.07       0
  5018.5    0.07       0  5549.7    0.07       0
Bank Sta=4985.9,5018.5
Exp/Cntr=0.3,0.1

Type RM Length L Ch R = 1,42000,1000,1000,1000
BEGIN DESCRIPTION:
Sweetwater Creek 83.0
END DESCRIPTION:
XS GIS Cut Line= 4
      1456417.09      6905785.97      1459104.91      6903698.16
      1461548.13      6903441.46      1462505.00      6902888.00
#Sta/Elev= 30
  -860.1 1824.56  -841.4 1827.79  -520.9 1821.87   305.8 1818.88   582.3 1817.39
  1631.7 1815.30  1787.8 1808.98  1916.3 1815.66  2044.8 1810.52  2059.3 1813.65
  2258.4 1815.21  2480.1 1809.74  2563.5 1816.09  3202.7 1816.67  3291.0 1817.13
  3594.0 1817.03  3951.0 1816.37  4866.1 1817.77  4956.6 1808.95  4982.9 1798.96
  4983.2 1796.96  5015.5 1798.96  5036.8 1809.88  5042.6 1807.29  5133.1 1816.16
  5145.7 1816.16  5951.3 1818.49  6067.6 1824.14  6089.5 1824.87  6105.4 1825.69
#Mann=14,-1,0
  -860.1    0.07       0   305.8   0.035       0   582.3    0.07       0
  3202.7   0.035       0  3291.0    0.07       0  3594.0   0.035       0
  3951.0    0.07       0  4982.9    0.07       0  5015.5    0.07       0
  5133.1    0.07       0  5145.7   0.035       0  5951.3    0.07       0
  6067.6   0.035       0  6089.5    0.07       0
Bank Sta=4982.9,5015.5
Exp/Cntr=0.3,0.1

Type RM Length L Ch R = 1,41000,3798,3798,3798
BEGIN DESCRIPTION:
Sweetwater Creek 81.0
END DESCRIPTION:
XS GIS Cut Line= 4
      1456448.44      6906607.93      1461455.20      6904350.85
      1461593.12      6904317.36      1462768.94      6902806.39
#Sta/Elev= 30
  -492.0 1833.14  -277.4 1831.61   -59.6 1829.70    61.2 1829.18   143.1 1829.19
   340.9 1825.96   776.7 1825.88  1674.1 1817.15  1784.3 1817.10  1891.0 1816.65
  1901.5 1816.58  2854.4 1811.56  2906.2 1815.40  3004.2 1805.10  3021.9 1809.02
  3178.9 1812.61  3573.8 1815.28  4758.5 1814.87  4844.8 1807.63  4905.9 1807.76
  4971.4 1808.18  4977.8 1805.74  4983.2 1794.30  4983.5 1792.30  5015.8 1794.30
  5029.4 1806.57  5087.9 1815.51  6676.0 1816.72  7013.8 1824.39  7056.5 1826.59
#Mann=16,-1,0
  -492.0    0.07       0  -277.4    0.16       0   -59.6    0.07       0
    61.2    0.16       0   143.1   0.035       0   340.9    0.07       0
  1674.1    0.16       0  1784.3    0.07       0  1891.0    0.16       0
  1901.5    0.07       0  4905.9    0.16       0  4983.2    0.07       0
  5015.8    0.16       0  5087.9   0.035       0  6676.0    0.07       0
  7013.8   0.035       0
Bank Sta=4983.2,5015.8
Exp/Cntr=0.3,0.1

Type RM Length L Ch R = 1,37202,3756,3756,3756
BEGIN DESCRIPTION:
Sweetwater Creek 72.0
END DESCRIPTION:
XS GIS Cut Line= 5
      1459341.63      6907676.89      1461206.86      6906294.86
      1462600.87      6905048.20      1462691.87      6904324.17
      1463193.19      6902706.26
#Sta/Elev= 30
    78.7 1835.89   235.5 1833.57   959.5 1821.19  1929.3 1820.03  1980.7 1820.07
  2143.9 1817.81  2268.0 1818.08  2468.2 1808.09  2657.7 1804.75  2684.3 1805.02
  2707.9 1799.06  2736.3 1809.30  3005.5 1813.42  4061.2 1813.74  4420.2 1807.56
  4623.2 1809.69  4875.2 1803.31  4902.6 1795.97  4965.9 1803.48  4976.0 1801.46
  4982.8 1792.33  4983.1 1790.33  5015.4 1792.33  5024.8 1805.82  5062.6 1813.72
  5138.0 1814.35  5155.8 1814.67  6046.9 1814.88  6367.4 1815.54  6693.8 1825.74
#Mann=13,-1,0
    78.7   0.035       0   235.5    0.07       0  1929.3   0.035       0
  1980.7    0.07       0  2143.9   0.035       0  2468.2    0.07       0
  2657.7    0.16       0  2684.3    0.07       0  4982.8    0.07       0
  5015.4    0.07       0  5138.0    0.07       0  5155.8   0.035       0
  6046.9    0.07       0
Bank Sta=4982.8,5015.4
Exp/Cntr=0.3,0.1

Type RM Length L Ch R = 1,33446,946,946,946
BEGIN DESCRIPTION:
Sweetwater Creek 66.0
END DESCRIPTION:
XS GIS Cut Line= 5
      1460947.93      6907305.34      1461802.35      6906435.43
      1462337.19      6906437.80      1463134.06      6906306.38
      1464321.09      6905759.66
#Sta/Elev= 30
  3478.1 1818.53  3837.2 1817.93  3958.4 1815.91  4358.0 1806.42  4450.0 1802.99
  4471.2 1797.57  4485.3 1802.82  4534.9 1806.49  4880.1 1810.51  4940.1 1800.07
  4960.1 1799.44  4970.1 1795.96  4981.7 1787.22  4982.0 1785.22  5014.4 1787.22
  5020.1 1797.75  5030.1 1799.55  5130.1 1797.66  5280.7 1805.81  5368.3 1804.57
  5670.8 1808.36  6061.5 1810.57  6185.1 1810.94  6187.8 1810.86  6352.3 1810.72
  6551.4 1812.71  6591.4 1817.52  6620.3 1813.84  6835.1 1822.34  7346.8 1830.51
#Mann=12,-1,0
  3478.1    0.07       0  3837.2   0.045       0  3958.4    0.07       0
  4981.7    0.07       0  5014.4    0.07       0  5368.3   0.035       0
  5670.8    0.07       0  6061.5   0.035       0  6185.1    0.07       0
  6187.8   0.035       0  6352.3    0.07       0  6835.1   0.035       0
Bank Sta=4981.7,5014.4
Exp/Cntr=0.3,0.1

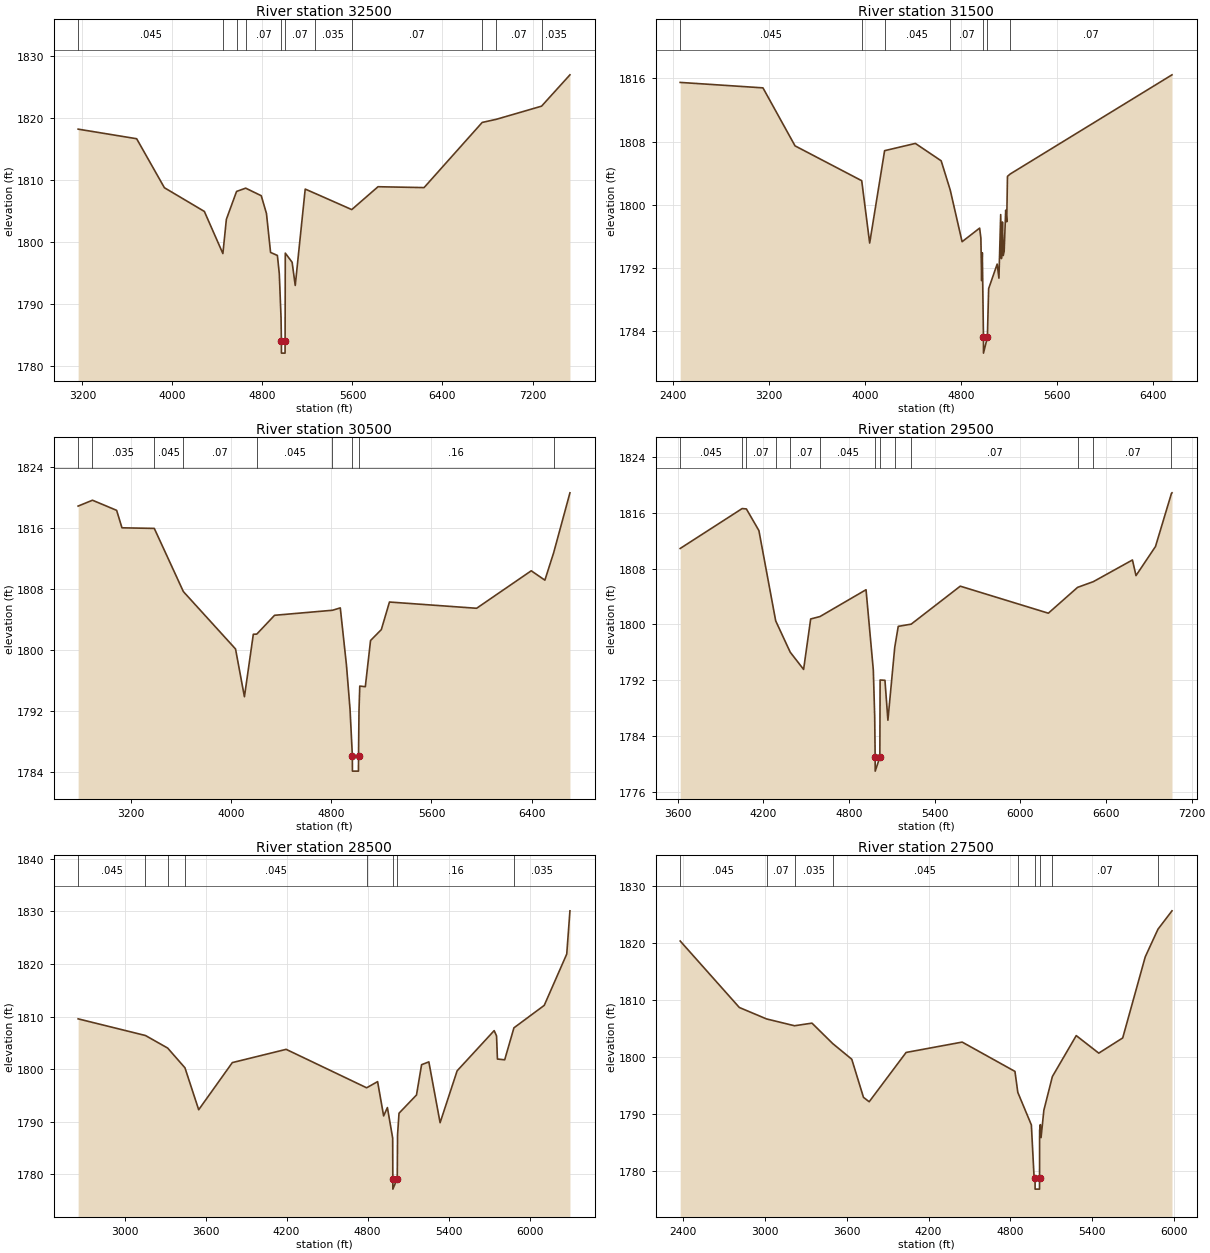
Type RM Length L Ch R = 1,32500,1000,1000,1000
BEGIN DESCRIPTION:
Sweetwater Creek 64.0
END DESCRIPTION:
XS GIS Cut Line= 3
      1461004.96      6907738.02      1462707.30      6907044.19
      1464956.13      6905879.14
#Sta/Elev= 30
  3161.7 1818.18  3681.9 1816.63  3928.4 1808.72  4283.6 1804.89  4448.2 1798.09
  4479.2 1803.62  4569.8 1808.12  4650.8 1808.65  4789.1 1807.43  4835.5 1804.56
  4872.0 1798.27  4932.7 1797.78  4949.5 1794.86  4965.1 1787.70  4968.4 1784.01
  4968.7 1782.01  5000.8 1782.01  5001.1 1784.01  5002.8 1798.16  5063.6 1796.68
  5091.3 1792.94  5179.9 1808.50  5265.6 1807.82  5593.5 1805.19  5826.9 1808.88
  6236.2 1808.74  6752.7 1819.26  6879.1 1819.77  7280.5 1821.89  7532.7 1826.95
#Mann=11,-1,0
  3161.7   0.045       0  4448.2    0.07       0  4569.8   0.045       0
  4650.8    0.07       0  4968.4    0.07       0  5001.1    0.07       0
  5265.6   0.035       0  5593.5    0.07       0  6752.7   0.035       0
  6879.1    0.07       0  7280.5   0.035       0
Bank Sta=4968.4,5001.1
Exp/Cntr=0.3,0.1

Type RM Length L Ch R = 1,31500,1000,1000,1000
BEGIN DESCRIPTION:
Sweetwater Creek 62.0
END DESCRIPTION:
XS GIS Cut Line= 3
      1461075.75      6908450.51      1463356.36      6907330.92
      1464616.36      6906414.71
#Sta/Elev= 30
  2459.4 1815.50  3149.2 1814.81  3416.6 1807.47  3972.2 1803.06  4038.5 1795.17
  4162.9 1806.86  4419.2 1807.78  4634.3 1805.58  4710.0 1801.87  4808.6 1795.34
  4954.7 1797.06  4965.1 1795.83  4971.6 1790.42  4977.2 1793.94  4986.7 1783.24
  4987.0 1781.24  5019.4 1783.24  5029.9 1789.40  5101.0 1792.51  5115.6 1790.73
  5130.3 1798.77  5136.5 1793.21  5145.0 1797.83  5151.2 1793.59  5159.1 1794.10
  5172.1 1799.33  5180.6 1797.86  5186.7 1803.61  5209.6 1803.91  6557.9 1816.46
#Mann=7,-1,0
  2459.4   0.045       0  3972.2    0.07       0  4162.9   0.045       0
  4710.0    0.07       0  4986.7    0.07       0  5019.4    0.07       0
  5209.6    0.07       0
Bank Sta=4986.7,5019.4
Exp/Cntr=0.3,0.1

Type RM Length L Ch R = 1,30500,1000,1000,1000
BEGIN DESCRIPTION:
Sweetwater Creek 60.0
END DESCRIPTION:
XS GIS Cut Line= 3
      1462120.70      6909667.84      1463755.17      6908168.51
      1464754.98      6906788.03
#Sta/Elev= 30
  2782.0 1818.93  2896.5 1819.70  3089.1 1818.37  3131.6 1816.08  3389.5 1816.00
  3621.4 1807.71  4037.4 1800.18  4108.3 1793.91  4179.2 1802.11  4206.8 1802.13
  4348.8 1804.60  4810.7 1805.26  4872.9 1805.57  4922.3 1798.02  4950.6 1792.28
  4969.2 1786.15  4969.6 1784.15  5017.8 1784.15  5018.2 1786.15  5022.2 1792.19
  5028.4 1795.31  5072.5 1795.23  5114.2 1801.29  5200.1 1802.72  5265.0 1806.34
  5960.2 1805.52  6395.9 1810.44  6504.6 1809.21  6574.6 1812.81  6704.5 1820.67
#Mann=9,-1,0
  2782.0   0.045       0  2896.5   0.035       0  3389.5   0.045       0
  3621.4    0.07       0  4206.8   0.045       0  4810.7    0.07       0
  4969.2    0.07       0  5018.2    0.16       0  6574.6   0.035       0
Bank Sta=4969.2,5018.2
Exp/Cntr=0.3,0.1

Type RM Length L Ch R = 1,29500,1000,1000,1000
BEGIN DESCRIPTION:
Sweetwater Creek 58.0
END DESCRIPTION:
XS GIS Cut Line= 4
      1463349.99      6909789.27      1464254.38      6909050.09
      1464284.89      6908838.01      1464810.30      6906844.18
#Sta/Elev= 30
  3617.7 1810.89  4051.6 1816.62  4081.3 1816.57  4169.0 1813.46  4286.6 1800.50
  4388.1 1796.01  4482.0 1793.53  4531.5 1800.77  4596.8 1801.12  4919.2 1804.97
  4970.2 1793.44  4979.8 1786.79  4983.1 1780.93  4983.4 1778.93  5015.9 1780.93
  5017.8 1792.01  5051.7 1791.97  5072.4 1786.24  5120.2 1796.70  5144.8 1799.71
  5235.5 1800.03  5579.1 1805.48  6195.9 1801.60  6400.7 1805.31  6511.2 1806.13
  6784.9 1809.24  6809.8 1807.00  6946.2 1811.17  7058.3 1818.81  7061.9 1818.88
#Mann=13,-1,0
  3617.7   0.045       0  4051.6   0.035       0  4081.3    0.07       0
  4286.6   0.045       0  4388.1    0.07       0  4596.8   0.045       0
  4983.1    0.07       0  5015.9    0.12       0  5120.2    0.12       0
  5235.5    0.07       0  6400.7   0.035       0  6511.2    0.07       0
  7058.3   0.035       0
Bank Sta=4983.1,5015.9
Exp/Cntr=0.3,0.1

Type RM Length L Ch R = 1,28500,1000,1000,1000
BEGIN DESCRIPTION:
Sweetwater Creek 56.0
END DESCRIPTION:
XS GIS Cut Line= 4
      1463437.09      6910090.96      1465090.12      6908818.22
      1465205.56      6908587.97      1465689.98      6907383.76
#Sta/Elev= 30
  2656.2 1809.56  3155.0 1806.39  3319.4 1804.00  3447.2 1800.25  3548.9 1792.28
  3798.0 1801.24  4196.6 1803.76  4792.6 1796.45  4873.7 1797.62  4918.4 1791.10
  4946.3 1792.69  4985.4 1786.89  4986.4 1779.18  4986.7 1777.18  5019.2 1779.18
  5021.5 1787.49  5032.3 1791.61  5161.7 1795.08  5199.4 1800.84  5253.2 1801.38
  5336.5 1789.81  5462.7 1799.68  5736.8 1807.32  5754.5 1806.31  5761.0 1801.92
  5814.8 1801.77  5883.2 1807.85  6107.6 1812.12  6274.3 1821.88  6298.0 1830.10
#Mann=8,-1,0
  2656.2   0.045       0  3155.0   0.035       0  3319.4    0.07       0
  3447.2   0.045       0  4792.6    0.07       0  4986.4    0.07       0
  5019.2    0.16       0  5883.2   0.035       0
Bank Sta=4986.4,5019.2
Exp/Cntr=0.3,0.1

Type RM Length L Ch R = 1,27500,1000,1000,1000
BEGIN DESCRIPTION:
Sweetwater Creek 54.0
END DESCRIPTION:
XS GIS Cut Line= 5
      1463238.32      6910851.59      1464639.60      6909671.76
      1465019.15      6909341.19      1465301.87      6909327.68
      1466255.00      6909088.00
#Sta/Elev= 30
  2381.8 1820.40  2814.9 1808.72  3014.0 1806.71  3218.9 1805.51  3346.8 1805.97
  3499.0 1802.37  3638.1 1799.63  3723.9 1792.93  3765.6 1792.16  4036.0 1800.82
  4446.5 1802.64  4832.9 1797.49  4853.9 1793.80  4953.1 1788.09  4973.1 1778.84
  4980.2 1778.81  4980.5 1776.81  5012.7 1776.81  5013.0 1778.81  5013.5 1787.10
  5018.9 1788.14  5024.1 1785.86  5044.5 1790.66  5106.8 1796.58  5281.6 1803.78
  5446.6 1800.70  5621.9 1803.37  5786.9 1817.61  5879.8 1822.46  5982.8 1825.70
#Mann=9,-1,0
  2381.8   0.045       0  3014.0    0.07       0  3218.9   0.035       0
  3499.0   0.045       0  4853.9    0.07       0  4980.2    0.07       0
  5013.0    0.07       0  5106.8    0.07       0  5879.8   0.035       0
Bank Sta=4980.2,5013
Exp/Cntr=0.3,0.1

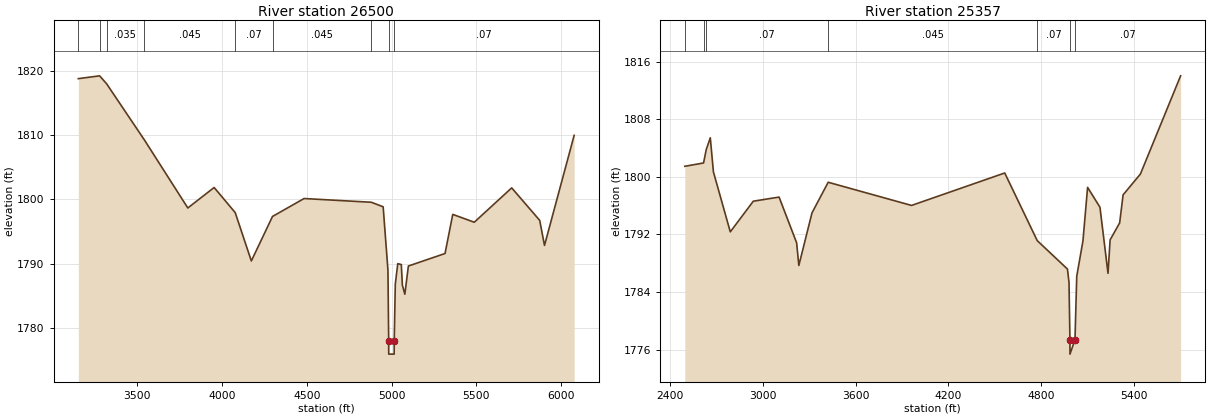
Type RM Length L Ch R = 1,26500,1143,1143,1143
BEGIN DESCRIPTION:
Sweetwater Creek 52.0
END DESCRIPTION:
XS GIS Cut Line= 4
      1463834.35      6911480.74      1465174.85      6910207.80
      1465346.73      6909972.78      1466058.76      6909638.87
#Sta/Elev= 30
  3151.4 1818.81  3276.9 1819.25  3317.8 1818.03  3540.7 1809.29  3797.6 1798.67
  3952.9 1801.86  4077.3 1797.95  4172.5 1790.42  4297.4 1797.35  4483.6 1800.14
  4880.7 1799.56  4950.4 1798.85  4978.7 1788.98  4983.0 1777.91  4983.3 1775.91
  5015.4 1775.91  5015.7 1777.91  5022.0 1786.81  5036.7 1790.00  5057.5 1789.86
  5063.7 1786.67  5078.4 1785.24  5099.2 1789.63  5315.5 1791.58  5361.2 1797.67
  5488.1 1796.45  5709.0 1801.80  5874.3 1796.74  5902.6 1792.84  6077.6 1809.98
#Mann=9,-1,0
  3151.4   0.035       0  3276.9   0.045       0  3317.8   0.035       0
  3540.7   0.045       0  4077.3    0.07       0  4297.4   0.045       0
  4880.7    0.07       0  4983.0    0.07       0  5015.7    0.07       0
Bank Sta=4983,5015.7
Exp/Cntr=0.3,0.1

Type RM Length L Ch R = 1,25357,1388,1388,1388
BEGIN DESCRIPTION:
Sweetwater Creek 50.0
END DESCRIPTION:
XS GIS Cut Line= 6
      1464261.65      6911863.68      1464791.67      6911790.49
      1465893.30      6910777.73      1466026.78      6910526.76
      1466036.30      6910126.08      1466255.02      6909687.96
#Sta/Elev= 30
  2495.2 1801.46  2616.5 1801.92  2634.0 1803.79  2660.1 1805.42  2680.3 1800.68
  2789.4 1792.35  2938.2 1796.61  3104.9 1797.18  3218.4 1790.83  3232.6 1787.68
  3317.6 1794.98  3422.4 1799.24  3961.3 1796.02  4564.1 1800.53  4774.2 1791.13
  4969.7 1787.18  4979.7 1785.32  4985.6 1777.36  4985.9 1775.36  5018.3 1777.36
  5029.7 1786.18  5069.8 1791.09  5099.8 1798.53  5179.8 1795.77  5231.9 1786.59
  5245.5 1791.24  5307.1 1793.59  5329.4 1797.49  5441.3 1800.38  5701.4 1814.03
#Mann=7,-1,0
  2495.2   0.035       0  2616.5   0.045       0  2634.0    0.07       0
  3422.4   0.045       0  4774.2    0.07       0  4985.6    0.07       0
  5018.3    0.07       0
Bank Sta=4985.6,5018.3
Exp/Cntr=0.3,0.1