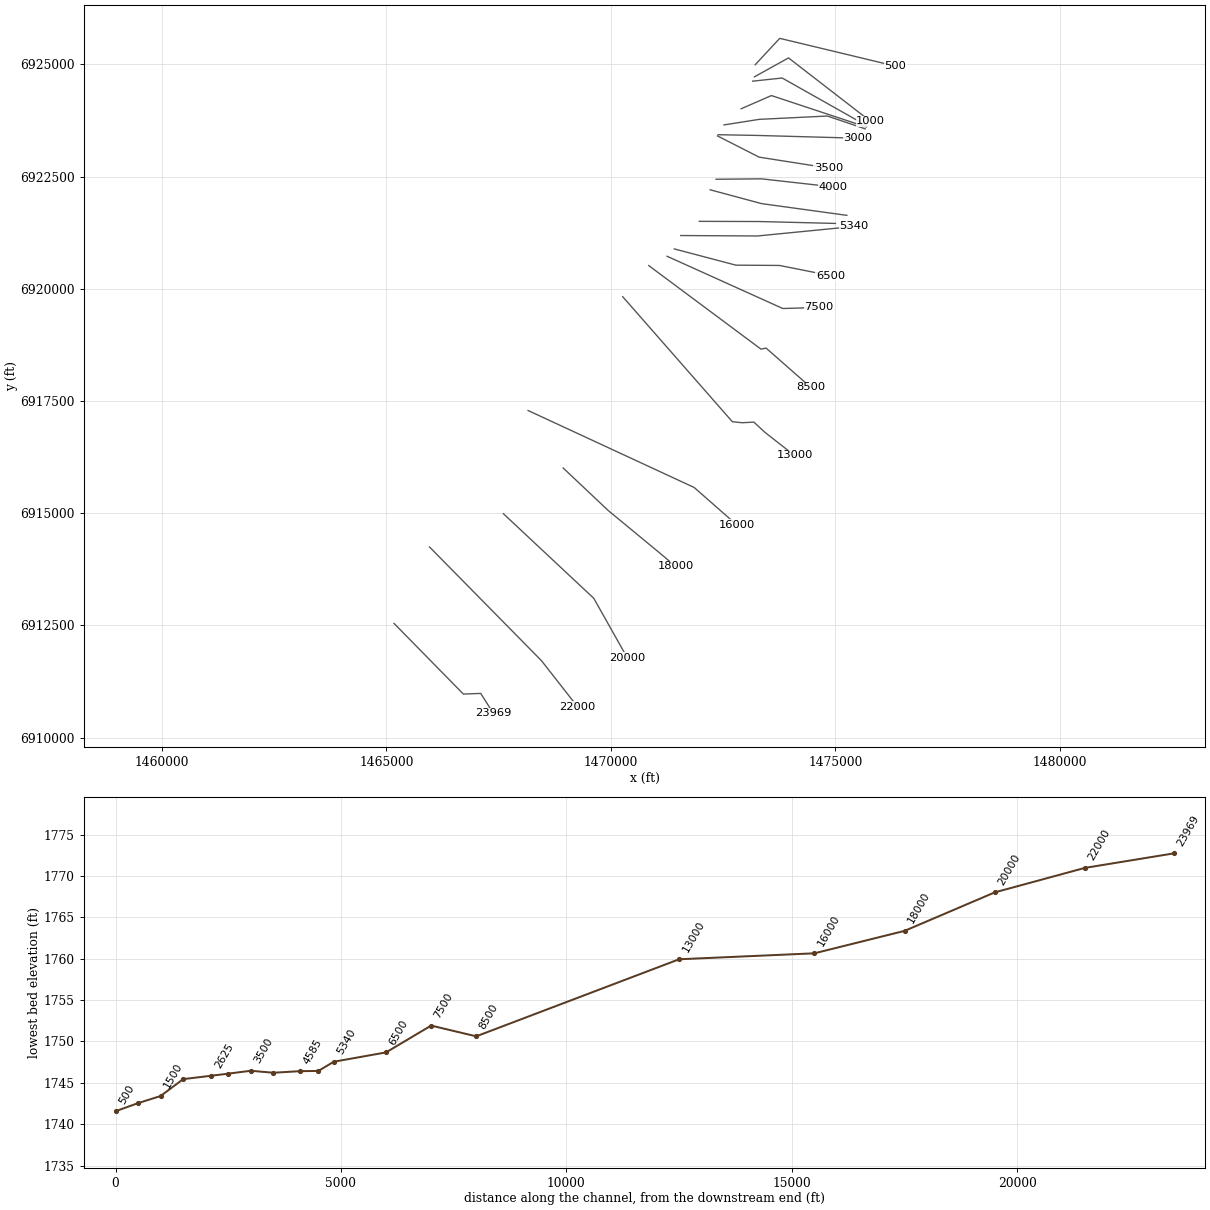
HEC-RAS study Sweetwater Creek.prj: Sweetwater Creek Base Level Engineering

--- Sweetwater Creek.g01 (geometry) --- (continued)

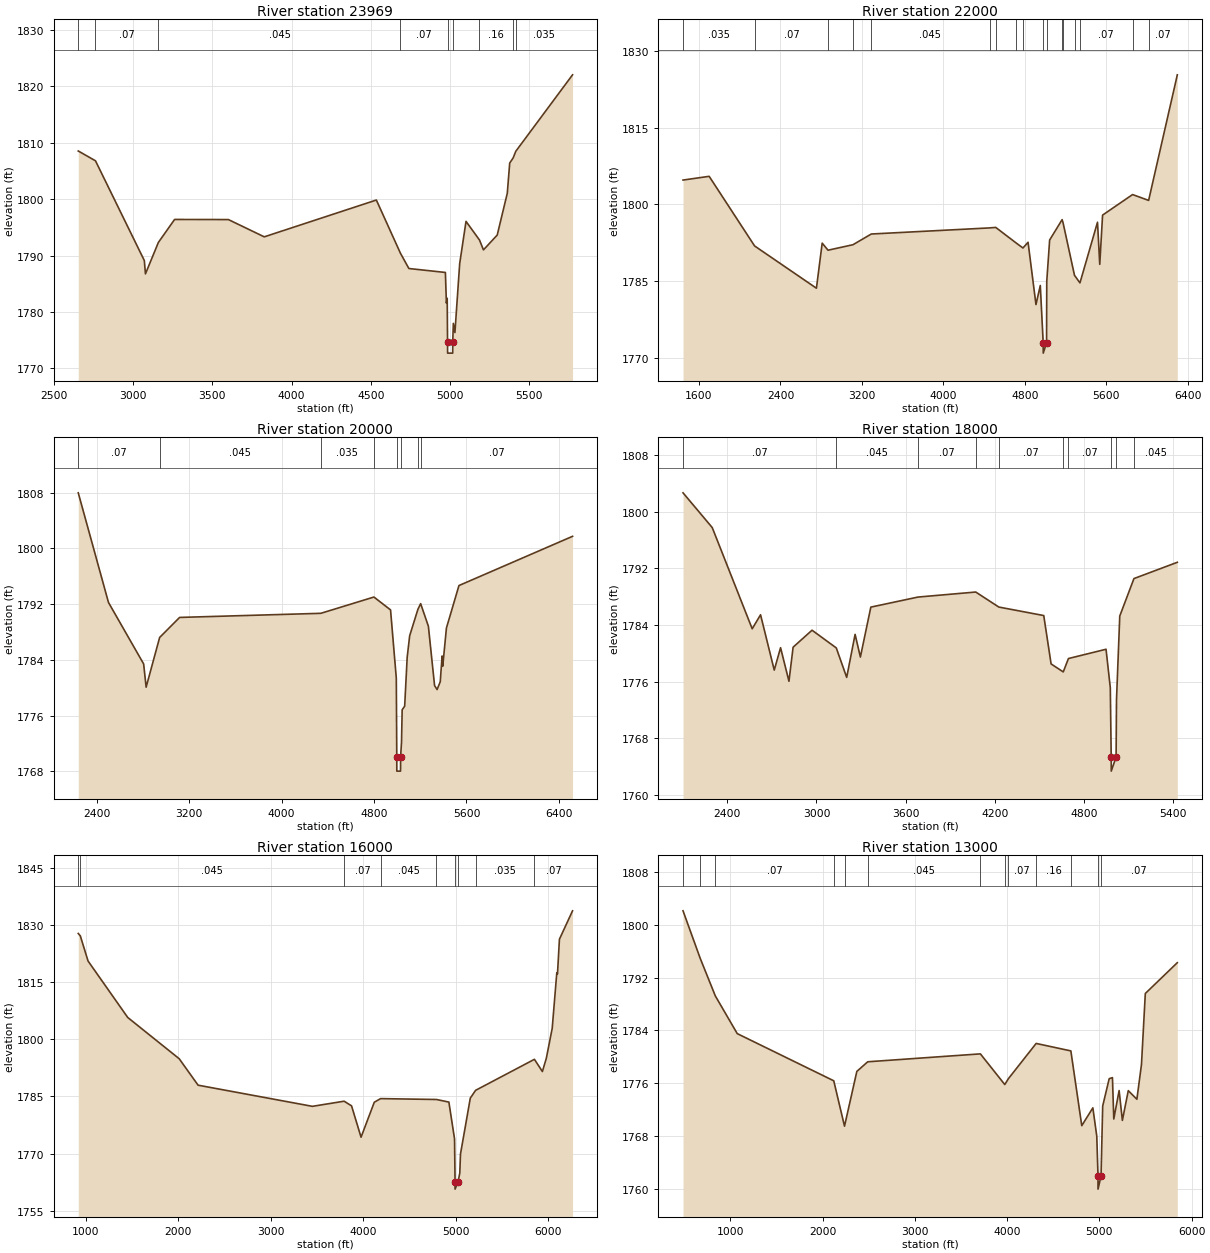
Type RM Length L Ch R = 1,23969,1969,1969,1969
BEGIN DESCRIPTION:
Sweetwater Creek 47.0
END DESCRIPTION:
XS GIS Cut Line= 4
      1465169.72      6912542.14      1466713.23      6910968.45
      1467099.48      6910983.16      1467382.51      6910538.17
#Sta/Elev= 30
  2653.9 1808.53  2762.6 1806.79  3070.7 1789.12  3077.8 1786.76  3159.4 1792.33
  3261.7 1796.40  3601.0 1796.38  3827.3 1793.32  4534.5 1799.84  4686.7 1790.40
  4739.6 1787.71  4970.0 1787.01  4976.3 1781.58  4981.4 1782.44  4983.6 1774.72
  4983.9 1772.72  5016.1 1772.72  5016.4 1774.72  5020.1 1777.99  5030.1 1776.37
  5060.1 1788.57  5100.1 1796.06  5185.1 1792.76  5210.2 1791.01  5297.0 1793.64
  5360.5 1801.05  5375.7 1806.39  5397.8 1807.32  5414.2 1808.48  5772.1 1822.02
#Mann=9,-1,0
  2653.9   0.035       0  2762.6    0.07       0  3159.4   0.045       0
  4686.7    0.07       0  4983.6    0.07       0  5016.4    0.07       0
  5185.1    0.16       0  5397.8    0.07       0  5414.2   0.035       0
Bank Sta=4983.6,5016.4
Exp/Cntr=0.3,0.1

Type RM Length L Ch R = 1,22000,2000,2000,2000
BEGIN DESCRIPTION:
Sweetwater Creek 43.0
END DESCRIPTION:
XS GIS Cut Line= 3
      1465960.04      6914246.19      1468454.72      6911710.68
      1469255.01      6910687.99
#Sta/Elev= 30
  1443.0 1804.75  1699.8 1805.48  2146.1 1791.89  2753.4 1783.64  2810.0 1792.44
  2867.5 1791.06  3112.5 1792.13  3292.5 1794.22  4453.8 1795.41  4514.8 1795.51
  4716.7 1792.45  4782.2 1791.49  4832.4 1792.61  4910.1 1780.45  4952.6 1784.17
  4981.2 1772.97  4981.5 1770.97  5014.0 1772.97  5016.1 1784.99  5044.4 1793.05
  5166.9 1797.02  5175.4 1796.49  5288.6 1786.16  5342.1 1784.68  5514.6 1796.52
  5536.7 1788.30  5564.4 1797.91  5859.0 1801.92  6016.8 1800.78  6298.6 1825.29
#Mann=17,-1,0
  1443.0   0.035       0  2146.1    0.07       0  2867.5   0.045       0
  3112.5   0.035       0  3292.5   0.045       0  4453.8   0.035       0
  4514.8   0.045       0  4716.7   0.035       0  4782.2    0.07       0
  4981.2    0.07       0  5014.0    0.07       0  5166.9   0.035       0
  5175.4    0.07       0  5288.6   0.035       0  5342.1    0.07       0
  5859.0   0.035       0  6016.8    0.07       0
Bank Sta=4981.2,5014
Exp/Cntr=0.3,0.1

Type RM Length L Ch R = 1,20000,2000,2000,2000
BEGIN DESCRIPTION:
Sweetwater Creek 39.0
END DESCRIPTION:
XS GIS Cut Line= 3
      1467604.99      6914988.01      1469618.96      6913101.97
      1470363.27      6911778.74
#Sta/Elev= 30
  2240.8 1807.99  2502.4 1792.24  2806.7 1783.41  2828.2 1780.07  2945.1 1787.21
  3117.9 1790.09  4340.1 1790.68  4799.4 1793.02  4943.3 1791.17  4993.1 1781.36
  4997.2 1770.01  4997.5 1768.01  5029.7 1768.01  5030.0 1770.01  5038.1 1772.13
  5043.8 1776.82  5065.5 1777.34  5087.2 1784.36  5108.8 1787.46  5180.2 1791.26
  5203.8 1792.07  5270.7 1788.83  5324.3 1780.30  5346.0 1779.73  5373.4 1780.85
  5389.3 1784.55  5395.0 1783.09  5426.9 1788.57  5535.3 1794.67  6518.2 1801.74
#Mann=8,-1,0
  2240.8    0.07       0  2945.1   0.045       0  4340.1   0.035       0
  4799.4    0.07       0  4997.2    0.07       0  5030.0    0.07       0
  5180.2    0.16       0  5203.8    0.07       0
Bank Sta=4997.2,5030
Exp/Cntr=0.3,0.1

Type RM Length L Ch R = 1,18000,2000,2000,2000
BEGIN DESCRIPTION:
Sweetwater Creek 35.0
END DESCRIPTION:
XS GIS Cut Line= 4
      1468936.09      6916007.36      1469937.98      6915061.21
      1471110.66      6914092.93      1471438.98      6913815.25
#Sta/Elev= 30
  2101.2 1802.66  2298.0 1797.75  2567.0 1783.46  2623.3 1785.44  2715.5 1777.63
  2758.0 1780.79  2814.6 1776.05  2842.5 1780.86  2970.0 1783.26  3133.3 1780.76
  3203.4 1776.60  3260.0 1782.67  3295.6 1779.47  3366.0 1786.52  3683.4 1787.94
  4072.6 1788.65  4227.8 1786.53  4530.5 1785.33  4580.0 1778.50  4661.8 1777.37
  4696.8 1779.26  4950.0 1780.57  4978.7 1775.13  4984.8 1765.36  4985.1 1763.36
  5017.7 1765.36  5020.4 1773.42  5042.4 1785.26  5137.9 1790.55  5430.0 1792.85
#Mann=10,-1,0
  2101.2    0.07       0  3133.3   0.045       0  3683.4    0.07       0
  4072.6   0.035       0  4227.8    0.07       0  4661.8    0.16       0
  4696.8    0.07       0  4984.8    0.07       0  5017.7    0.16       0
  5137.9   0.045       0
Bank Sta=4984.8,5017.7
Exp/Cntr=0.3,0.1

Type RM Length L Ch R = 1,16000,3000,3000,3000
BEGIN DESCRIPTION:
Sweetwater Creek 31.0
END DESCRIPTION:
XS GIS Cut Line= 3
      1468154.99      6917288.00      1471855.01      6915572.43
      1472804.99      6914738.01
#Sta/Elev= 30
   921.6 1827.85   943.9 1827.22  1027.5 1820.61  1456.4 1805.77  2012.9 1794.92
  2217.0 1787.97  3452.4 1782.41  3795.5 1783.76  3875.7 1782.54  3978.4 1774.30
  4121.4 1783.49  4189.9 1784.44  4793.6 1784.21  4927.8 1783.53  4989.0 1773.85
  4994.5 1762.65  4994.8 1760.65  5027.4 1762.65  5045.6 1764.87  5053.2 1769.88
  5159.4 1784.58  5216.7 1786.62  5852.4 1794.77  5938.5 1791.56  5981.2 1795.06
  6044.8 1802.94  6094.1 1817.51  6101.7 1817.22  6122.6 1826.33  6264.4 1833.80
#Mann=9,-1,0
   921.6    0.07       0   943.9   0.045       0  3795.5    0.07       0
  4189.9   0.045       0  4793.6    0.07       0  4994.5    0.07       0
  5027.4    0.16       0  5216.7   0.035       0  5852.4    0.07       0
Bank Sta=4994.5,5027.4
Exp/Cntr=0.3,0.1

Type RM Length L Ch R = 1,13000,4500,4500,4500
BEGIN DESCRIPTION:
Sweetwater Creek 25.0
END DESCRIPTION:
XS GIS Cut Line= 6
      1470262.36      6919824.82      1472705.00      6917038.00
      1472922.46      6917015.95      1473184.41      6917029.33
      1473424.24      6916806.83      1474089.07      6916285.77
#Sta/Elev= 30
   486.2 1802.11   673.0 1794.89   836.4 1789.21  1074.0 1783.50  2120.2 1776.35
  2236.8 1769.47  2370.4 1777.77  2488.4 1779.23  3709.8 1780.43  3974.3 1775.78
  4014.1 1776.68  4314.4 1782.01  4690.6 1780.88  4808.9 1769.55  4929.1 1772.25
  4971.6 1767.96  4984.9 1761.93  4985.2 1759.93  5017.8 1761.93  5035.7 1772.52
  5106.2 1776.67  5141.5 1776.83  5155.9 1770.56  5213.8 1774.87  5249.1 1770.35
  5313.2 1774.86  5406.3 1773.55  5456.1 1778.81  5497.7 1789.58  5844.7 1794.25
#Mann=13,-1,0
   486.2    0.07       0   673.0   0.035       0   836.4    0.07       0
  2120.2   0.035       0  2236.8    0.07       0  2488.4   0.045       0
  3709.8    0.07       0  3974.3    0.16       0  4014.1    0.07       0
  4314.4    0.16       0  4690.6    0.07       0  4984.9    0.07       0
  5017.8    0.07       0
Bank Sta=4984.9,5017.8
Exp/Cntr=0.3,0.1

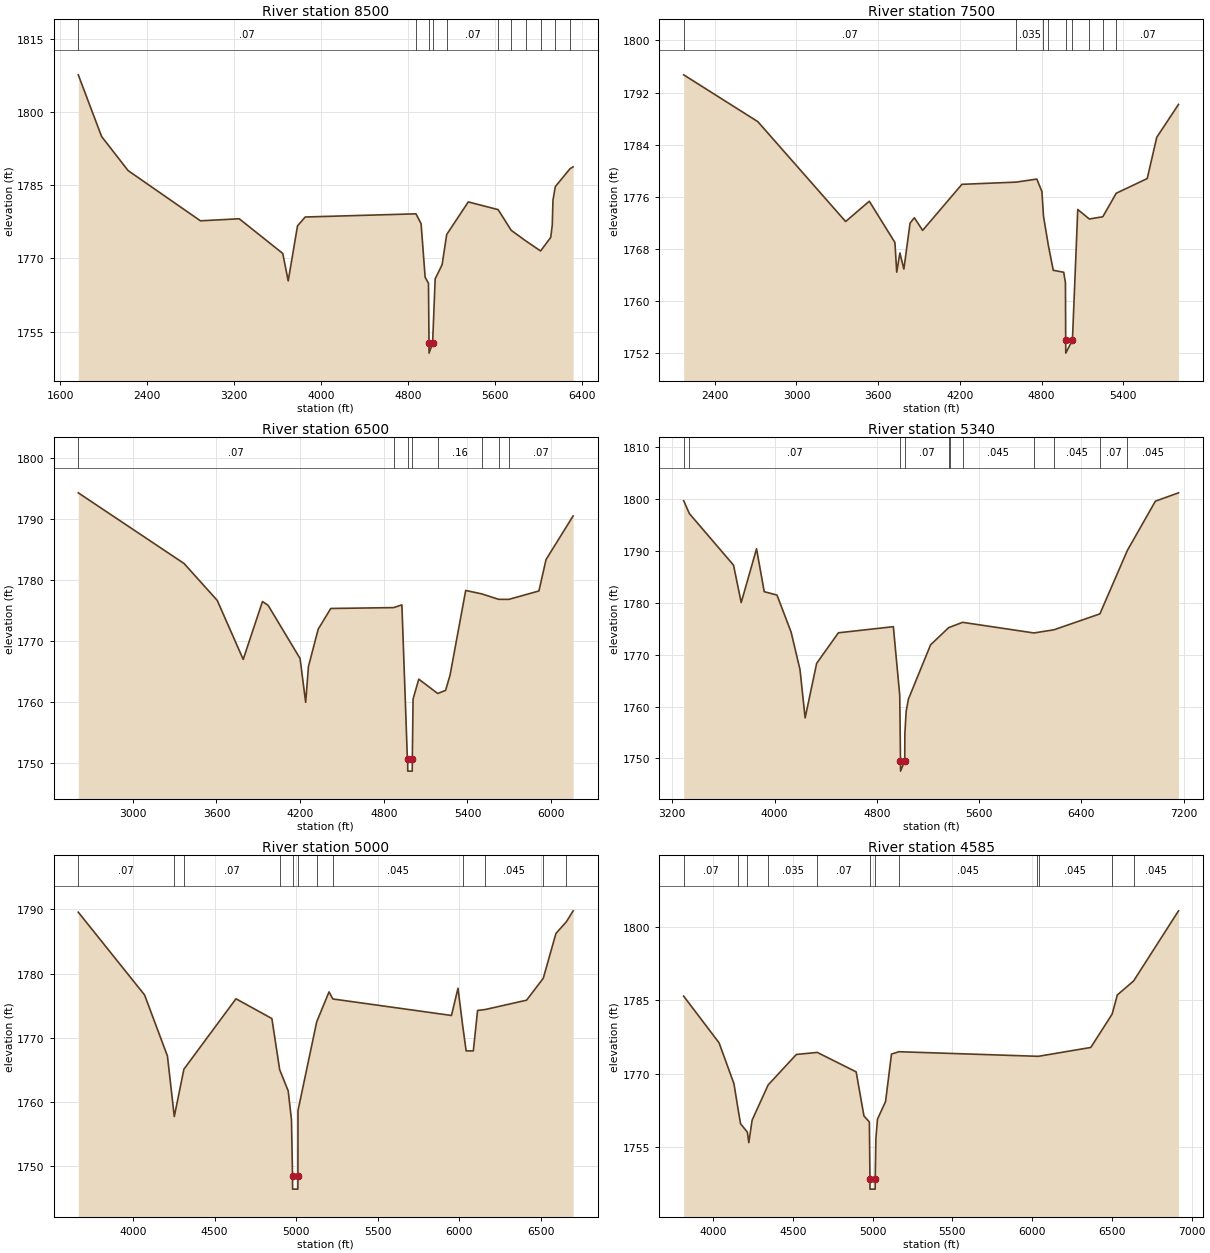
Type RM Length L Ch R = 1,8500,1000,1000,1000
BEGIN DESCRIPTION:
Sweetwater Creek 16.0
END DESCRIPTION:
XS GIS Cut Line= 4
      1470843.22      6920517.53      1473342.80      6918655.99
      1473456.63      6918679.32      1474446.64      6917808.35
#Sta/Elev= 30
  1767.2 1807.60  1981.7 1794.97  2225.7 1787.99  2890.9 1777.71  3247.5 1778.13
  3647.9 1771.03  3698.0 1765.41  3783.5 1776.67  3854.3 1778.49  4873.0 1779.14
  4920.2 1777.12  4957.5 1766.16  4988.1 1764.92  4993.1 1752.62  4993.4 1750.62
  5026.1 1752.62  5049.7 1765.83  5113.3 1768.71  5155.8 1774.91  5354.3 1781.58
  5628.8 1780.00  5748.9 1775.77  5884.2 1773.58  6019.4 1771.54  6112.4 1774.31
  6126.6 1776.83  6133.2 1781.95  6154.7 1784.71  6290.0 1788.38  6318.6 1788.76
#Mann=11,-1,0
  1767.2    0.07       0  4873.0    0.16       0  4993.1    0.07       0
  5026.1    0.16       0  5155.8    0.07       0  5628.8   0.035       0
  5748.9    0.16       0  5884.2    0.07       0  6019.4    0.16       0
  6154.7    0.07       0  6290.0   0.035       0
Bank Sta=4993.1,5026.1
Exp/Cntr=0.3,0.1

Type RM Length L Ch R = 1,7500,1000,1000,1000
BEGIN DESCRIPTION:
Sweetwater Creek 14.0
END DESCRIPTION:
XS GIS Cut Line= 3
      1471250.80      6920725.95      1473828.61      6919561.55
      1474634.88      6919584.61
#Sta/Elev= 30
  2171.4 1794.72  2716.1 1787.52  3361.1 1772.16  3535.0 1775.28  3723.2 1768.93
  3736.5 1764.37  3759.6 1767.33  3789.0 1764.85  3834.4 1771.91  3865.8 1772.74
  3926.9 1770.80  4215.3 1777.88  4614.0 1778.22  4765.6 1778.69  4803.1 1776.77
  4814.5 1772.99  4850.1 1768.52  4886.3 1764.66  4963.1 1764.36  4975.9 1762.73
  4977.7 1753.92  4978.2 1751.92  5027.2 1753.92  5066.4 1774.01  5151.1 1772.55
  5250.1 1772.89  5349.1 1776.51  5576.6 1778.77  5646.7 1785.11  5806.6 1790.17
#Mann=9,-1,0
  2171.4    0.07       0  4614.0   0.035       0  4814.5    0.07       0
  4850.1    0.16       0  4977.7    0.07       0  5027.2    0.16       0
  5151.1    0.07       0  5250.1   0.035       0  5349.1    0.07       0
Bank Sta=4977.7,5027.2
Exp/Cntr=0.3,0.1

Type RM Length L Ch R = 1,6500,1160,1160,1160
BEGIN DESCRIPTION:
Sweetwater Creek 12.0
END DESCRIPTION:
XS GIS Cut Line= 4
      1471411.47      6920889.72      1472783.04      6920527.66
      1473755.17      6920521.16      1474890.57      6920295.06
#Sta/Elev= 30
  2609.3 1794.31  3368.0 1782.72  3605.8 1776.67  3792.0 1767.00  3930.1 1776.49
  3970.4 1775.87  4199.8 1767.14  4239.8 1759.96  4259.8 1765.85  4329.8 1771.96
  4419.8 1775.35  4870.8 1775.49  4929.8 1775.94  4969.8 1750.25  4971.5 1750.68
  4971.8 1748.68  5004.2 1748.68  5004.5 1750.68  5010.0 1760.50  5050.8 1763.76
  5186.7 1761.41  5243.0 1761.92  5275.1 1764.41  5387.3 1778.30  5502.8 1777.74
  5623.5 1776.85  5696.8 1776.84  5912.3 1778.22  5963.4 1783.37  6157.7 1790.52
#Mann=8,-1,0
  2609.3    0.07       0  4870.8    0.16       0  4971.5    0.07       0
  5004.5    0.16       0  5186.7    0.16       0  5502.8    0.07       0
  5623.5    0.16       0  5696.8    0.07       0
Bank Sta=4971.5,5004.5
Exp/Cntr=0.3,0.1

Type RM Length L Ch R = 1,5340,340,340,340
BEGIN DESCRIPTION:
Sweetwater Creek 10.0
END DESCRIPTION:
XS GIS Cut Line= 3
      1471554.99      6921188.00      1473265.47      6921178.18
      1475415.17      6921389.89
#Sta/Elev= 30
  3289.5 1799.67  3334.1 1797.19  3679.5 1787.25  3739.5 1780.04  3859.5 1790.40
  3919.5 1782.14  4019.5 1781.48  4129.5 1774.37  4199.5 1767.10  4239.5 1757.81
  4329.5 1768.32  4499.5 1774.21  4929.5 1775.39  4979.5 1762.16  4985.4 1749.55
  4985.7 1747.55  5018.4 1749.55  5019.6 1754.78  5029.7 1759.08  5047.0 1761.41
  5220.6 1771.89  5361.9 1775.20  5372.0 1775.30  5471.3 1776.23  6029.0 1774.18
  6185.6 1774.79  6545.1 1777.86  6759.5 1790.07  6979.1 1799.58  7160.1 1801.19
#Mann=11,-1,0
  3289.5   0.035       0  3334.1    0.07       0  4985.4    0.07       0
  5018.4    0.07       0  5361.9   0.045       0  5372.0    0.07       0
  5471.3   0.045       0  6029.0    0.07       0  6185.6   0.045       0
  6545.1    0.07       0  6759.5   0.045       0
Bank Sta=4985.4,5018.4
Exp/Cntr=0.3,0.1

Type RM Length L Ch R = 1,5000,415,415,415
BEGIN DESCRIPTION:
Sweetwater Creek 9.0
END DESCRIPTION:
XS GIS Cut Line= 3
      1471968.78      6921504.13      1473303.88      6921500.03
      1475000.25      6921457.72
#Sta/Elev= 30
  3664.9 1789.58  4071.1 1776.69  4211.1 1767.18  4253.2 1757.75  4312.0 1765.12
  4631.1 1776.09  4851.1 1773.01  4898.8 1765.05  4951.1 1761.74  4971.1 1757.26
  4977.7 1748.44  4978.0 1746.44  5010.4 1746.44  5010.7 1748.44  5011.1 1758.68
  5125.8 1772.50  5201.2 1777.16  5224.9 1776.06  5951.4 1773.49  5991.4 1777.73
  6020.2 1771.90  6041.4 1767.97  6085.3 1767.97  6111.5 1774.27  6159.1 1774.42
  6411.6 1775.87  6514.0 1779.29  6591.6 1786.27  6655.9 1788.10  6696.9 1789.79
#Mann=12,-1,0
  3664.9    0.07       0  4253.2    0.16       0  4312.0    0.07       0
  4898.8    0.16       0  4977.7    0.07       0  5010.7    0.07       0
  5125.8    0.07       0  5224.9   0.045       0  6020.2    0.07       0
  6159.1   0.045       0  6514.0    0.07       0  6655.9   0.045       0
Bank Sta=4977.7,5010.7
Exp/Cntr=0.3,0.1

Type RM Length L Ch R = 1,4585,585,585,585
BEGIN DESCRIPTION:
Sweetwater Creek 8.0
END DESCRIPTION:
XS GIS Cut Line= 3
      1472210.71      6922207.69      1473354.99      6921899.34
      1475255.00      6921638.00
#Sta/Elev= 30
  3814.9 1785.83  4036.8 1776.30  4130.0 1767.96  4153.6 1763.24  4171.5 1759.77
  4214.3 1758.05  4223.3 1755.90  4244.0 1760.50  4344.7 1767.70  4521.6 1773.92
  4652.6 1774.34  4896.4 1770.37  4945.3 1761.37  4979.3 1760.13  4983.0 1748.41
  4983.3 1746.41  5015.7 1746.41  5016.0 1748.41  5020.2 1756.78  5030.3 1760.71
  5080.8 1764.30  5118.0 1774.00  5164.4 1774.48  6028.2 1773.55  6040.5 1773.55
  6367.6 1775.35  6501.4 1782.15  6534.3 1786.08  6636.5 1788.95  6917.9 1803.26
#Mann=12,-1,0
  3814.9    0.07       0  4153.6    0.16       0  4214.3    0.07       0
  4344.7   0.035       0  4652.6    0.07       0  4983.0    0.07       0
  5016.0    0.16       0  5164.4   0.045       0  6028.2    0.07       0
  6040.5   0.045       0  6501.4    0.07       0  6636.5   0.045       0
Bank Sta=4983,5016
Exp/Cntr=0.3,0.1

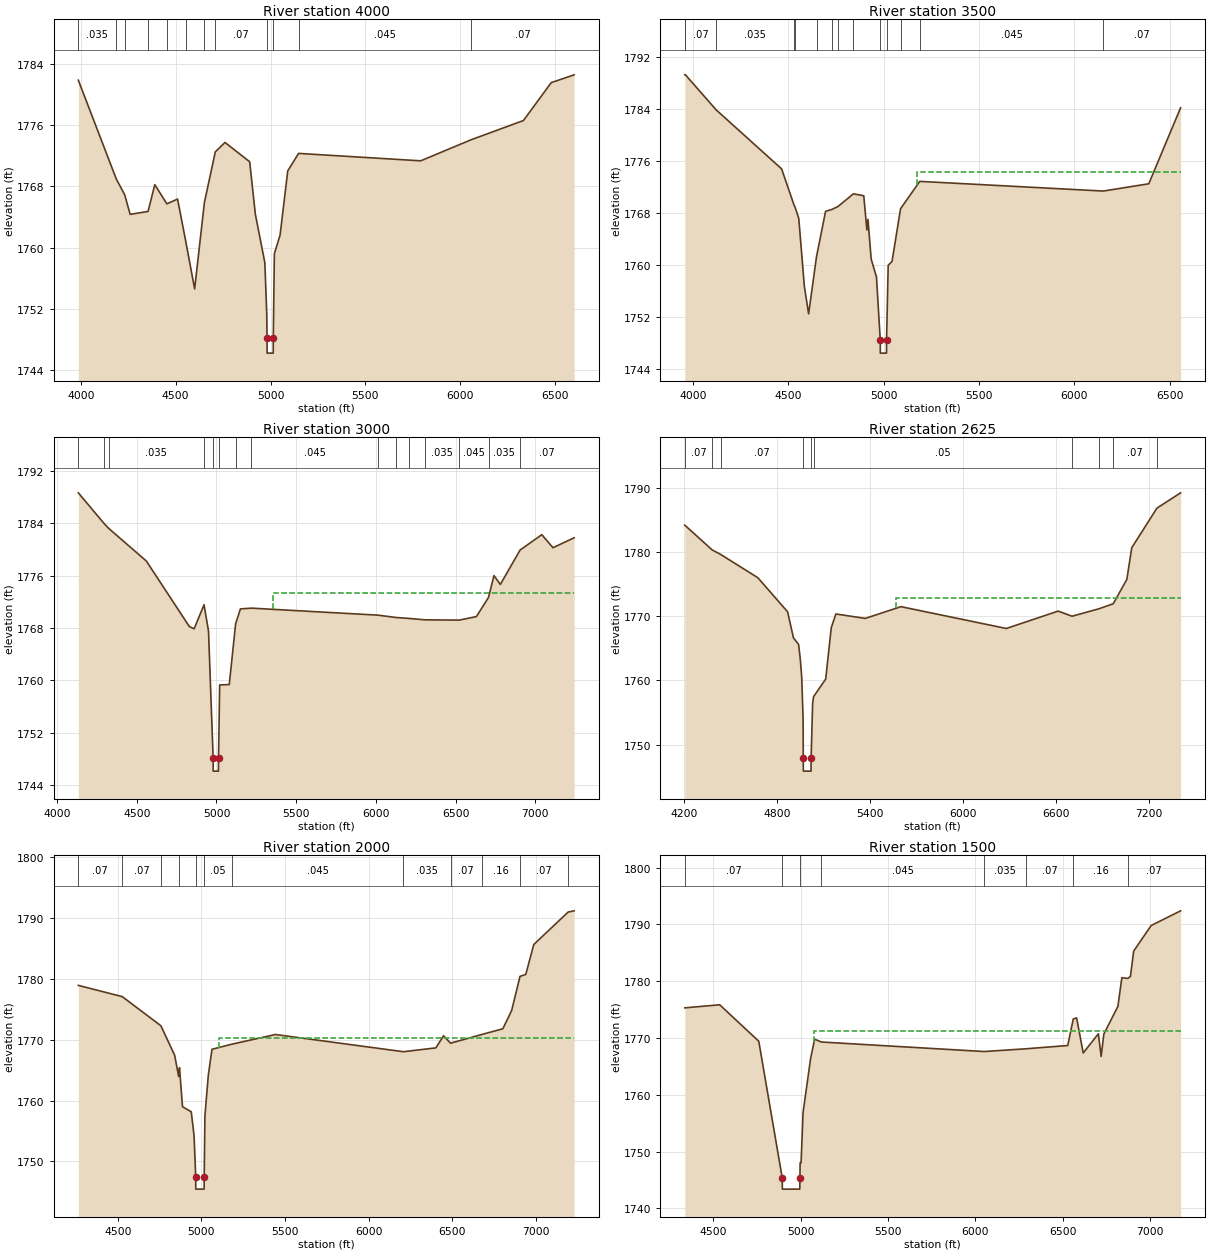
Type RM Length L Ch R = 1,4000,500,500,500
BEGIN DESCRIPTION:
Sweetwater Creek 7.0
END DESCRIPTION:
XS GIS Cut Line= 3
      1472342.04      6922442.07      1473355.00      6922451.23
      1474945.16      6922273.20
#Sta/Elev= 30
  3987.0 1781.86  4187.2 1768.95  4231.5 1766.89  4260.0 1764.34  4354.5 1764.72
  4390.0 1768.22  4453.5 1765.71  4510.0 1766.34  4552.5 1760.90  4600.0 1754.61
  4651.5 1765.90  4708.9 1772.50  4760.0 1773.73  4890.0 1771.21  4920.0 1764.35
  4970.0 1758.03  4980.0 1751.37  4981.5 1748.22  4981.8 1746.22  5014.2 1746.22
  5014.5 1748.22  5020.1 1759.19  5050.3 1761.64  5090.6 1770.01  5147.9 1772.30
  5791.4 1771.33  6059.0 1774.10  6332.8 1776.59  6479.2 1781.54  6600.1 1782.56
#Mann=12,-1,0
  3987.0   0.035       0  4187.2    0.07       0  4231.5   0.035       0
  4354.5    0.07       0  4453.5    0.16       0  4552.5    0.07       0
  4651.5    0.16       0  4708.9    0.07       0  4981.5    0.05       0
  5014.5    0.07       0  5147.9   0.045       0  6059.0    0.07       0
Bank Sta=4981.5,5014.5
Exp/Cntr=0.3,0.1

Type RM Length L Ch R = 1,3500,500,500,500
BEGIN DESCRIPTION:
Sweetwater Creek 6.0
END DESCRIPTION:
XS GIS Cut Line= 5
      1472372.67      6923408.40      1472618.65      6923283.00
      1472805.00      6923188.00      1473301.80      6922934.74
      1474839.85      6922693.87
#Sta/Elev= 30
  3957.1 1789.27  3960.5 1789.27  4121.9 1783.87  4464.8 1774.80  4529.4 1769.28
  4535.1 1768.92  4554.6 1767.20  4584.1 1756.71  4606.3 1752.50  4647.9 1761.33
  4695.2 1768.27  4728.6 1768.57  4760.7 1769.02  4840.9 1770.96  4895.4 1770.67
  4912.0 1765.39  4917.6 1767.04  4934.2 1760.95  4962.1 1758.16  4982.0 1748.46
  4982.3 1746.46  5014.7 1746.46  5015.0 1748.46  5023.5 1759.97  5043.7 1760.56
  5088.4 1768.67  5189.1 1772.88  6151.0 1771.39  6389.9 1772.51  6556.8 1784.21
#Mann=14,-1,0
  3957.1   0.035       0  3960.5    0.07       0  4121.9   0.035       0
  4529.4    0.07       0  4535.1    0.16       0  4647.9    0.12       0
  4728.6    0.16       0  4760.7    0.07       0  4840.9    0.12       0
  4982.0    0.05       0  5015.0    0.12       0  5088.4    0.07       0
  5189.1   0.045       0  6151.0    0.07       0
#XS Ineff=2,0
       0                 5174.40    0.00 1774.28
Permanent Ineff=
       F       F
Bank Sta=4982,5015
Exp/Cntr=0.3,0.1

Type RM Length L Ch R = 1,3000,375,375,375
BEGIN DESCRIPTION:
Sweetwater Creek 5.0
END DESCRIPTION:
XS GIS Cut Line= 5
      1472388.50      6923435.14      1472683.31      6923429.64
      1473254.95      6923418.96      1475002.74      6923370.77
      1475497.80      6923357.12
#Sta/Elev= 30
  4133.4 1788.68  4296.9 1783.93  4324.3 1783.23  4560.0 1778.25  4830.0 1768.22
  4860.0 1767.89  4921.9 1771.56  4950.0 1767.54  4979.1 1748.11  4979.4 1746.11
  5012.6 1746.11  5012.9 1748.11  5020.1 1759.29  5080.1 1759.35  5120.2 1768.66
  5150.1 1770.92  5219.3 1771.04  6012.4 1769.97  6127.0 1769.61  6210.7 1769.46
  6309.8 1769.25  6523.0 1769.21  6630.7 1769.75  6706.4 1772.68  6740.7 1776.02
  6780.7 1774.67  6904.7 1779.93  7040.8 1782.28  7110.9 1780.28  7243.7 1781.81
#Mann=15,-1,0
  4133.4   0.035       0  4296.9    0.07       0  4324.3   0.035       0
  4921.9    0.05       0  4979.1   0.035       0  5012.9    0.05       0
  5120.2    0.07       0  5219.3   0.045       0  6012.4   0.035       0
  6127.0   0.045       0  6210.7    0.07       0  6309.8   0.035       0
  6523.0   0.045       0  6706.4   0.035       0  6904.7    0.07       0
#XS Ineff=2,0
    0.00 4643.90 1773.29 5356.10    0.00 1773.29
Permanent Ineff=
       F       F
Bank Sta=4979.1,5012.9
Exp/Cntr=0.3,0.1

Type RM Length L Ch R = 1,2625,625,625,625
BEGIN DESCRIPTION:
Sweetwater Creek 4.0
END DESCRIPTION:
XS GIS Cut Line= 5
      1472518.50      6923653.59      1472665.13      6923676.66
      1473306.22      6923777.49      1474820.56      6923851.57
      1475664.24      6923565.84
#Sta/Elev= 30
  4202.6 1784.19  4379.6 1780.33  4433.7 1779.64  4674.8 1776.00  4867.2 1770.68
  4904.7 1766.63  4938.0 1765.60  4948.2 1763.52  4958.3 1760.46  4967.2 1753.91
  4968.2 1747.86  4968.7 1745.86  5018.5 1745.86  5018.9 1747.86  5028.8 1756.43
  5034.7 1757.46  5113.3 1760.21  5149.0 1768.20  5179.0 1770.35  5369.2 1769.66
  5599.5 1771.49  6280.3 1768.09  6615.9 1770.80  6705.1 1770.00  6879.3 1771.16
  6971.7 1771.95  7059.3 1775.73  7091.0 1780.67  7254.0 1786.85  7406.9 1789.23
#Mann=10,-1,0
  4202.6    0.07       0  4379.6   0.035       0  4433.7    0.07       0
  4968.2   0.035       0  5018.9    0.07       0  5034.7    0.05       0
  6705.1    0.07       0  6879.3    0.16       0  6971.7    0.07       0
  7254.0   0.035       0
#XS Ineff=2,0
       0                 5565.90    0.00 1772.91
Permanent Ineff=
       F       F
Bank Sta=4968.2,5018.9
Exp/Cntr=0.3,0.1

Type RM Length L Ch R = 1,2000,500,500,500
BEGIN DESCRIPTION:
Sweetwater Creek 3.0
END DESCRIPTION:
XS GIS Cut Line= 4
      1472901.03      6924013.29      1473574.83      6924307.42
      1475350.98      6923719.39      1475689.46      6923607.34
#Sta/Elev= 30
  4264.8 1778.96  4527.1 1777.11  4758.1 1772.32  4840.5 1767.46  4864.1 1763.99
  4869.3 1765.43  4887.3 1759.00  4939.6 1758.17  4956.5 1754.20  4966.2 1747.45
  4966.6 1745.45  5016.4 1745.45  5016.9 1747.45  5021.2 1757.52  5041.5 1764.19
  5063.4 1768.45  5181.1 1769.28  5442.6 1770.88  6207.1 1768.05  6401.2 1768.68
  6447.2 1770.67  6488.8 1769.45  6676.6 1770.89  6801.4 1771.82  6854.1 1774.83
  6904.0 1780.44  6938.4 1780.76  6986.3 1785.68  7191.6 1791.02  7227.5 1791.22
#Mann=12,-1,0
  4264.8    0.07       0  4527.1    0.07       0  4758.1    0.07       0
  4864.1    0.05       0  4966.2   0.035       0  5016.9    0.05       0
  5181.1   0.045       0  6207.1   0.035       0  6488.8    0.07       0
  6676.6    0.16       0  6904.0    0.07       0  7191.6   0.035       0
#XS Ineff=2,0
       0                 5104.70    0.00 1770.29
Permanent Ineff=
       F       F
Bank Sta=4966.2,5016.9
Exp/Cntr=0.3,0.1

Type RM Length L Ch R = 1,1500,500,500,500
BEGIN DESCRIPTION:
Sweetwater Creek 2.0
END DESCRIPTION:
XS GIS Cut Line= 5
      1473156.55      6924628.38      1473814.51      6924698.65
      1475178.25      6923929.10      1475474.57      6923761.89
      1475707.34      6923630.54
#Sta/Elev= 30
  4338.3 1775.32  4537.9 1775.86  4761.3 1769.44  4895.3 1745.41  4895.4 1745.19
  4896.2 1743.41  4995.8 1743.41  4996.7 1745.41  4997.7 1748.02  5003.2 1748.02
  5014.6 1756.89  5058.0 1766.48  5080.9 1769.80  5118.4 1769.31  6050.2 1767.63
  6287.2 1768.11  6527.7 1768.69  6559.7 1773.36  6578.8 1773.55  6616.4 1767.38
  6703.0 1770.75  6719.0 1766.78  6734.4 1770.71  6814.8 1775.58  6837.4 1780.63
  6871.3 1780.50  6886.5 1780.86  6905.0 1785.32  7004.9 1789.81  7173.4 1792.40
#Mann=8,-1,0
  4338.3    0.07       0  4895.4   0.035       0  4996.7    0.07       0
  5118.4   0.045       0  6050.2   0.035       0  6287.2    0.07       0
  6559.7    0.16       0  6871.3    0.07       0
#XS Ineff=2,0
       0                 5077.60    0.00 1771.26
Permanent Ineff=
       F       F
Bank Sta=4895.3,4996.7
Exp/Cntr=0.3,0.1

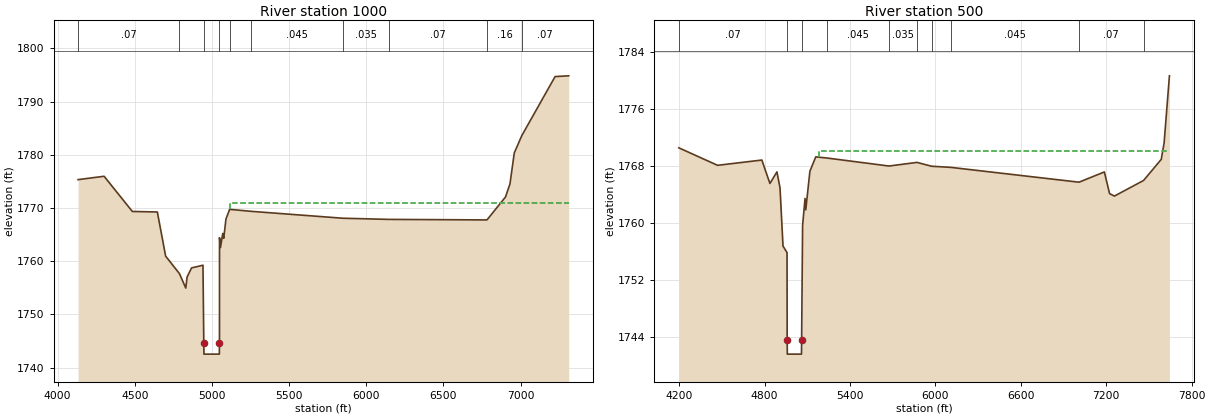
Type RM Length L Ch R = 1,1000,500,500,500
BEGIN DESCRIPTION:
Sweetwater Creek 1.0
END DESCRIPTION:
XS GIS Cut Line= 4
      1473197.54      6924725.57      1473955.76      6925146.65
      1475553.69      6923910.39      1475783.83      6923732.34
#Sta/Elev= 30
  4132.7 1775.33  4301.4 1775.96  4484.4 1769.35  4646.3 1769.25  4700.1 1760.96
  4789.5 1757.67  4830.5 1754.96  4839.0 1757.04  4868.2 1758.75  4941.9 1759.25
  4947.3 1744.55  4948.2 1742.55  5047.9 1742.55  5048.8 1744.55  5049.1 1764.43
  5055.5 1762.57  5070.0 1765.22  5076.3 1764.31  5090.8 1767.92  5114.7 1769.75
  5251.6 1769.38  5847.3 1768.08  6144.7 1767.86  6781.8 1767.76  6901.8 1772.07
  6930.8 1774.52  6958.8 1780.35  7007.9 1783.62  7223.2 1794.69  7311.3 1794.83
#Mann=10,-1,0
  4132.7    0.07       0  4789.5     0.1       0  4947.3   0.035       0
  5048.8     0.1       0  5114.7    0.07       0  5251.6   0.045       0
  5847.3   0.035       0  6144.7    0.07       0  6781.8    0.16       0
  7007.9    0.07       0
#XS Ineff=2,0
       0                 5116.90    0.00 1770.89
Permanent Ineff=
       F       F
Bank Sta=4947.3,5048.8
Exp/Cntr=0.3,0.1

Type RM Length L Ch R = 1,500,0,0,0
BEGIN DESCRIPTION:
Sweetwater Creek 2959
END DESCRIPTION:
XS GIS Cut Line= 3
      1473213.96      6924994.46      1473760.13      6925582.98
      1476330.76      6924965.31
#Sta/Elev= 30
  4197.1 1770.55  4469.3 1768.09  4780.5 1768.83  4837.2 1765.54  4886.5 1767.17
  4908.1 1764.93  4929.1 1756.75  4957.4 1755.83  4958.4 1743.57  4959.3 1741.57
  5059.0 1741.57  5059.9 1743.57  5066.7 1759.63  5083.8 1763.44  5089.0 1761.83
  5118.1 1767.26  5159.3 1769.28  5239.8 1769.11  5673.5 1767.99  5870.5 1768.50
  5973.1 1767.96  6108.9 1767.80  7008.8 1765.72  7186.7 1767.16  7223.5 1764.11
  7257.3 1763.77  7462.0 1765.96  7586.5 1768.93  7606.4 1771.23  7643.8 1780.66
#Mann=10,-1,0
  4197.1    0.07       0  4958.4   0.035       0  5059.9    0.07       0
  5239.8   0.045       0  5673.5   0.035       0  5870.5   0.045       0
  5973.1    0.07       0  6108.9   0.045       0  7008.8    0.07       0
  7462.0    0.16       0
#XS Ineff=2,0
       0                 5181.40    0.00 1770.08
Permanent Ineff=
       F       F
Bank Sta=4958.4,5059.9
Exp/Cntr=0.3,0.1

Chan Stop Cuts=-1