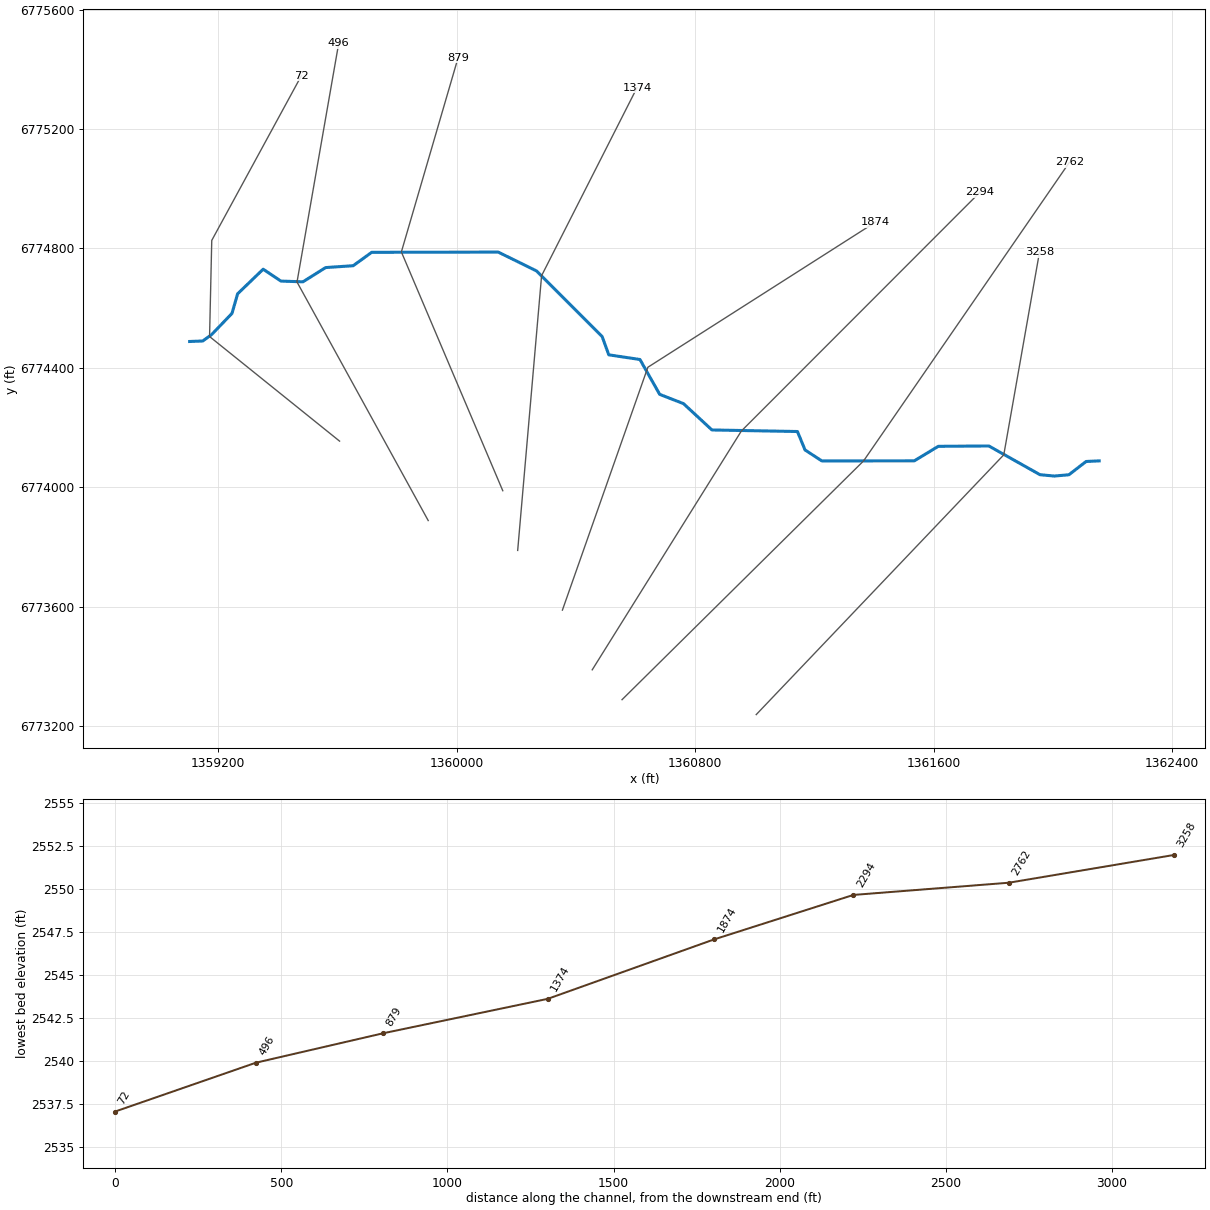
--- Sweetwater Creek Trib 1.prj (project) ---

Proj Title=Sweetwater Creek Trib 1 Base Level Engineering
Current Plan=p01
Default Exp/Contr=0.3,0.1
English Units
Geom File=g01
Flow File=f01
Plan File=p01
Y Axis Title=Elevation
X Axis Title(PF)=Main Channel Distance
X Axis Title(XS)=Station
BEGIN DESCRIPTION:
Sweetwater Creek Trib 1
END DESCRIPTION:
DSS Export Rating Curves= 0
DSS Export Rating Curve Sorted= 0
DSS Export Volume Flow Curves= 0
DXF OffsetX= 0
DXF OffsetY= 0
DXF ScaleX= 1
DXF ScaleY= 10

--- Sweetwater Creek Trib 1.p01 (plan) ---

Plan Title=Multiple Run
Short Identifier=Multiple
Geom File=g01
Flow File=f01
Subcritical Flow
K Sum by GR= 0
Std Step Tol= 0.01
Critical Tol= 0.01
Num of Std Step Trials= 20
Max Error Tol= 0.3
Flow Tol Ratio= 0.001
Split Flow NTrial= 30
Split Flow Tol= 0.02
Split Flow Ratio= 0.02
Log Output Level= 0
Friction Slope Method= 1
Unsteady Friction Slope Method= 2
Unsteady Bridges Friction Slope Method= 1
Parabolic Critical Depth
Global Vel Dist=  1 , 1 , 1
Global Log Level= 0
CheckData=True
Encroach Param= -1, 0, 0, 0
BEGIN DESCRIPTION:
Multiple Run
END DESCRIPTION:

--- Sweetwater Creek Trib 1.f01 (steady flow) ---

Flow Title=Multiple
Number of Profiles=7
Profile Names=10-year,25-year,50-year,1pct_min,100-year,1pct_plu,500-year
River Rch & RM= Sweetwater Creek,Reach-1,3258
     142     186     221     130     259     517     361
River Rch & RM= Sweetwater Creek,Reach-1,2762
     161     216     258     154     306     612     437
Boundary for River Rch & Prof#=Sweetwater Creek,Reach-1,1
Up Type=0
Dn Type=3
Dn Slope=0.005
Boundary for River Rch & Prof#=Sweetwater Creek,Reach-1,2
Up Type=0
Dn Type=3
Dn Slope=0.005
Boundary for River Rch & Prof#=Sweetwater Creek,Reach-1,3
Up Type=0
Dn Type=3
Dn Slope=0.005
Boundary for River Rch & Prof#=Sweetwater Creek,Reach-1,4
Up Type=0
Dn Type=3
Dn Slope=0.005
Boundary for River Rch & Prof#=Sweetwater Creek,Reach-1,5
Up Type=0
Dn Type=3
Dn Slope=0.005
Boundary for River Rch & Prof#=Sweetwater Creek,Reach-1,6
Up Type=0
Dn Type=3
Dn Slope=0.005
Boundary for River Rch & Prof#=Sweetwater Creek,Reach-1,7
Up Type=0
Dn Type=3
Dn Slope=0.005

--- Sweetwater Creek Trib 1.g01 (geometry) ---

Geom Title=Existing Conditions

River Reach=Sweetwater Creek,Reach-1
Reach XY= 30
      1362155.00      6774088.00      1362111.27      6774086.01
      1362053.47      6774041.52      1362005.00      6774037.17
      1361956.58      6774041.67      1361784.97      6774137.94
      1361615.51      6774136.78      1361534.97      6774088.07
      1361224.88      6774087.93      1361168.56      6774124.63
      1361143.17      6774186.36      1360856.47      6774191.55
      1360761.02      6774279.81      1360681.17      6774310.87
      1360615.06      6774427.60      1360510.48      6774443.26
      1360488.26      6774504.45      1360268.22      6774724.38
      1360139.79      6774787.49      1359715.50      6774786.78
      1359653.40      6774741.86      1359560.97      6774735.64
      1359484.90      6774687.91      1359410.89      6774690.37
      1359351.57      6774730.21      1359265.78      6774647.72
      1359246.86      6774581.94      1359178.52      6774511.02
      1359148.87      6774489.67      1359105.00      6774488.00

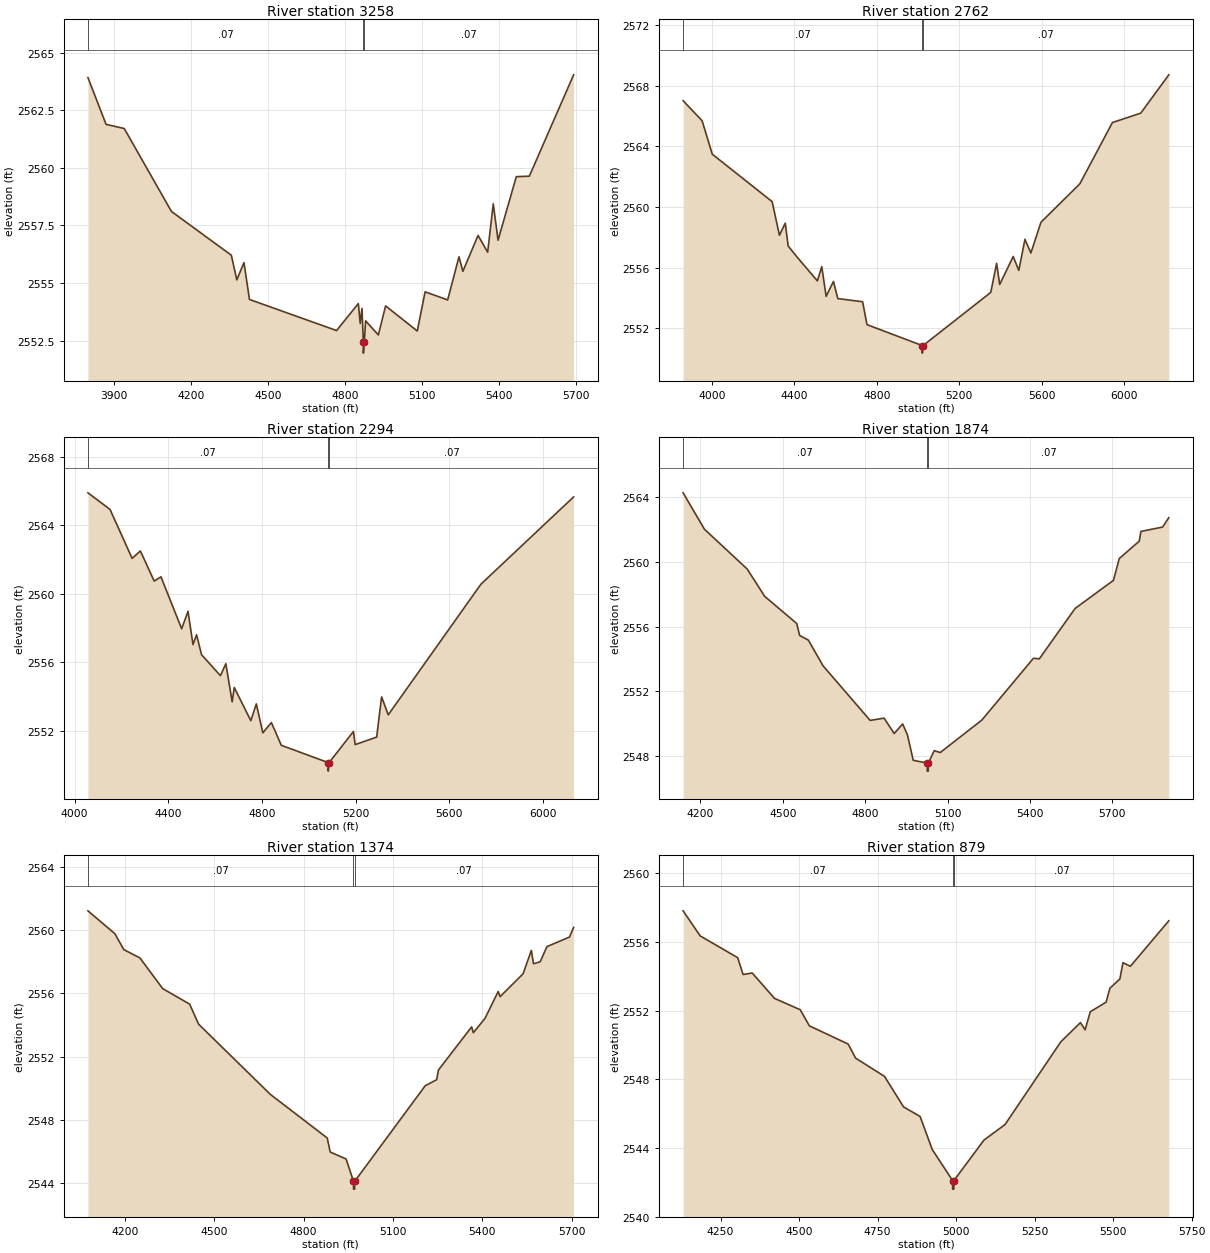
Type RM Length L Ch R = 1,3258,496,496,496
BEGIN DESCRIPTION:
Sweetwater Creek Trib 1 6.0
END DESCRIPTION:
XS GIS Cut Line= 3
      1361004.99      6773237.99      1361835.11      6774108.28
      1361955.00      6774787.98
#Sta/Elev= 30
  3797.3 2563.92  3867.9 2561.89  3938.7 2561.71  4122.7 2558.11  4356.1 2556.21
  4377.5 2555.14  4405.4 2555.89  4426.8 2554.29  4766.2 2552.94  4851.1 2554.11
  4858.4 2553.25  4865.3 2553.90  4870.5 2552.46  4870.8 2551.96  4874.5 2552.46
  4879.4 2553.36  4929.1 2552.75  4957.4 2554.01  5080.8 2552.92  5111.4 2554.62
  5199.3 2554.27  5243.4 2556.14  5258.5 2555.51  5317.8 2557.07  5355.1 2556.34
  5377.0 2558.44  5395.7 2556.86  5466.8 2559.62  5517.6 2559.64  5690.2 2564.04
#Mann=3,-1,0
  3797.3    0.07       0  4870.5    0.07       0  4874.5    0.07       0
Bank Sta=4870.5,4874.5
Exp/Cntr=0.3,0.1

Type RM Length L Ch R = 1,2762,468,468,468
BEGIN DESCRIPTION:
Sweetwater Creek Trib 1 5.0
END DESCRIPTION:
XS GIS Cut Line= 3
      1360554.97      6773287.97      1361365.00      6774087.99
      1362055.03      6775088.04
#Sta/Elev= 30
  3861.5 2567.01  3953.5 2565.69  4002.9 2563.48  4292.9 2560.35  4328.2 2558.13
  4356.5 2558.93  4370.6 2557.42  4413.1 2556.70  4512.1 2555.12  4533.3 2556.06
  4554.5 2554.10  4589.9 2555.08  4611.1 2553.95  4731.3 2553.74  4752.5 2552.23
  5020.3 2550.85  5020.6 2550.35  5024.4 2550.85  5352.3 2554.36  5380.6 2556.28
  5395.5 2554.88  5461.1 2556.73  5488.1 2555.81  5517.9 2557.86  5546.7 2556.96
  5595.6 2558.99  5783.6 2561.52  5941.8 2565.57  6079.1 2566.19  6215.0 2568.72
#Mann=3,-1,0
  3861.5    0.07       0  5020.3    0.07       0  5024.4    0.07       0
Bank Sta=5020.3,5024.4
Exp/Cntr=0.3,0.1

Type RM Length L Ch R = 1,2294,420,420,420
BEGIN DESCRIPTION:
Sweetwater Creek Trib 1 4.0
END DESCRIPTION:
XS GIS Cut Line= 3
      1360455.01      6773388.01      1360954.97      6774187.92
      1361754.97      6774987.97
#Sta/Elev= 30
  4056.7 2565.91  4151.0 2564.94  4245.4 2562.08  4280.7 2562.51  4339.7 2560.75
  4368.6 2561.00  4457.0 2557.96  4484.2 2558.98  4505.4 2557.04  4520.7 2557.61
  4541.9 2556.45  4622.7 2555.22  4645.7 2555.92  4672.8 2553.69  4681.7 2554.53
  4752.4 2552.59  4776.0 2553.57  4803.7 2551.88  4840.3 2552.48  4882.7 2551.15
  5082.9 2550.14  5083.1 2549.64  5087.0 2550.14  5191.0 2551.96  5198.1 2551.19
  5290.0 2551.63  5311.2 2553.98  5339.5 2552.93  5735.5 2560.57  6131.4 2565.67
#Mann=3,-1,0
  4056.7    0.07       0  5082.9    0.07       0  5087.0    0.07       0
Bank Sta=5082.9,5087
Exp/Cntr=0.3,0.1

Type RM Length L Ch R = 1,1874,500,500,500
BEGIN DESCRIPTION:
Sweetwater Creek Trib 1 3.0
END DESCRIPTION:
XS GIS Cut Line= 3
      1360355.00      6773587.99      1360641.53      6774401.61
      1361404.96      6774887.98
#Sta/Elev= 30
  4137.4 2564.28  4214.8 2562.03  4370.7 2559.56  4434.3 2557.87  4550.9 2556.19
  4561.5 2555.45  4593.3 2555.16  4646.3 2553.58  4818.0 2550.19  4868.9 2550.33
  4905.6 2549.38  4936.5 2549.97  4953.8 2549.30  4975.0 2547.72  5025.7 2547.55
  5026.0 2547.05  5029.6 2547.05  5029.9 2547.55  5051.5 2548.32  5073.2 2548.20
  5224.7 2550.21  5412.6 2554.04  5433.8 2554.00  5564.1 2557.12  5703.7 2558.86
  5724.9 2560.21  5797.7 2561.29  5803.7 2561.89  5882.4 2562.16  5905.2 2562.74
#Mann=3,-1,0
  4137.4    0.07       0  5025.7    0.07       0  5029.9    0.07       0
Bank Sta=5025.7,5029.9
Exp/Cntr=0.3,0.1

Type RM Length L Ch R = 1,1374,495,495,495
BEGIN DESCRIPTION:
Sweetwater Creek Trib 1 2.0
END DESCRIPTION:
XS GIS Cut Line= 3
      1360205.00      6773787.97      1360285.16      6774708.39
      1360605.00      6775338.01
#Sta/Elev= 30
  4076.1 2561.23  4166.5 2559.78  4196.6 2558.77  4250.4 2558.25  4327.1 2556.30
  4417.4 2555.32  4447.5 2554.05  4688.4 2549.60  4879.2 2546.84  4889.2 2545.95
  4942.5 2545.51  4967.3 2544.10  4967.6 2543.60  4971.3 2543.60  4971.6 2544.10
  5208.2 2550.15  5246.3 2550.53  5252.7 2551.15  5364.0 2553.88  5369.7 2553.51
  5408.5 2554.41  5453.1 2556.12  5459.4 2555.79  5536.5 2557.24  5564.3 2558.72
  5571.6 2557.88  5594.0 2558.00  5616.5 2558.96  5692.3 2559.57  5706.2 2560.18
#Mann=3,-1,0
  4076.1    0.07       0  4967.3    0.07       0  4971.6    0.07       0
Bank Sta=4967.3,4971.6
Exp/Cntr=0.3,0.1

Type RM Length L Ch R = 1,879,383,383,383
BEGIN DESCRIPTION:
Sweetwater Creek Trib 1 1.0
END DESCRIPTION:
XS GIS Cut Line= 3
      1360155.00      6773988.01      1359814.98      6774788.05
      1360005.01      6775438.04
#Sta/Elev= 30
  4130.7 2557.81  4185.0 2556.35  4304.5 2555.08  4321.6 2554.10  4350.7 2554.19
  4421.7 2552.71  4503.5 2552.05  4532.7 2551.11  4656.2 2550.05  4679.9 2549.23
  4771.8 2548.17  4832.6 2546.39  4885.4 2545.83  4923.9 2543.91  4988.7 2542.10
  4988.9 2541.60  4992.7 2541.60  4993.0 2542.10  5088.8 2544.46  5155.7 2545.36
  5333.3 2550.18  5395.9 2551.30  5410.7 2550.88  5427.1 2551.93  5477.6 2552.49
  5489.6 2553.30  5521.4 2553.84  5531.3 2554.79  5554.9 2554.58  5677.2 2557.23
#Mann=3,-1,0
  4130.7    0.07       0  4988.7    0.07       0  4993.0    0.07       0
Bank Sta=4988.7,4993
Exp/Cntr=0.3,0.1

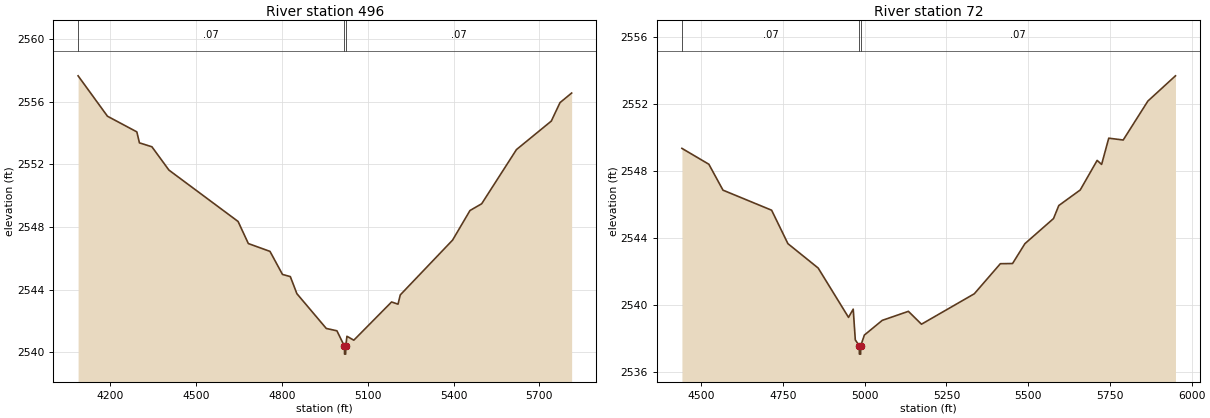
Type RM Length L Ch R = 1,496,424,424,424
BEGIN DESCRIPTION:
Sweetwater Creek Trib 1 2569
END DESCRIPTION:
XS GIS Cut Line= 3
      1359904.98      6773888.03      1359465.04      6774687.25
      1359605.00      6775488.01
#Sta/Elev= 30
  4087.7 2557.66  4190.4 2555.08  4293.1 2554.08  4302.1 2553.38  4345.7 2553.13
  4405.3 2551.64  4647.0 2548.36  4682.8 2546.95  4758.5 2546.45  4802.1 2544.98
  4829.6 2544.84  4852.5 2543.75  4955.2 2541.53  4992.4 2541.38  5018.9 2540.39
  5019.2 2539.89  5023.0 2539.89  5023.3 2540.39  5027.5 2541.03  5051.5 2540.78
  5183.5 2543.22  5206.0 2543.08  5213.9 2543.67  5396.7 2547.17  5457.6 2549.06
  5498.4 2549.49  5620.0 2552.95  5741.8 2554.77  5772.3 2555.95  5812.9 2556.56
#Mann=3,-1,0
  4087.7    0.07       0  5018.9    0.07       0  5023.3    0.07       0
Bank Sta=5018.9,5023.3
Exp/Cntr=0.3,0.1

Type RM Length L Ch R = 1,72,0,0,0
BEGIN DESCRIPTION:
Sweetwater Creek Trib 1 4368
END DESCRIPTION:
XS GIS Cut Line= 4
      1359607.70      6774154.19      1359171.75      6774504.56
      1359179.12      6774826.65      1359479.65      6775378.44
#Sta/Elev= 30
  4440.7 2549.36  4523.1 2548.41  4566.3 2546.86  4715.1 2545.66  4764.9 2543.66
  4857.5 2542.20  4950.3 2539.25  4964.7 2539.74  4971.1 2537.90  4983.3 2537.55
  4983.6 2537.05  4987.4 2537.05  4987.7 2537.55  4998.8 2538.19  5053.5 2539.07
  5133.5 2539.61  5173.5 2538.84  5335.1 2540.66  5414.8 2542.46  5452.1 2542.47
  5490.0 2543.66  5577.4 2545.16  5593.6 2545.94  5659.1 2546.87  5710.9 2548.64
  5724.6 2548.40  5746.4 2549.97  5790.6 2549.86  5866.1 2552.19  5950.5 2553.70
#Mann=3,-1,0
  4440.7    0.07       0  4983.3    0.07       0  4987.7    0.07       0
Bank Sta=4983.3,4987.7
Exp/Cntr=0.3,0.1

Chan Stop Cuts=-1