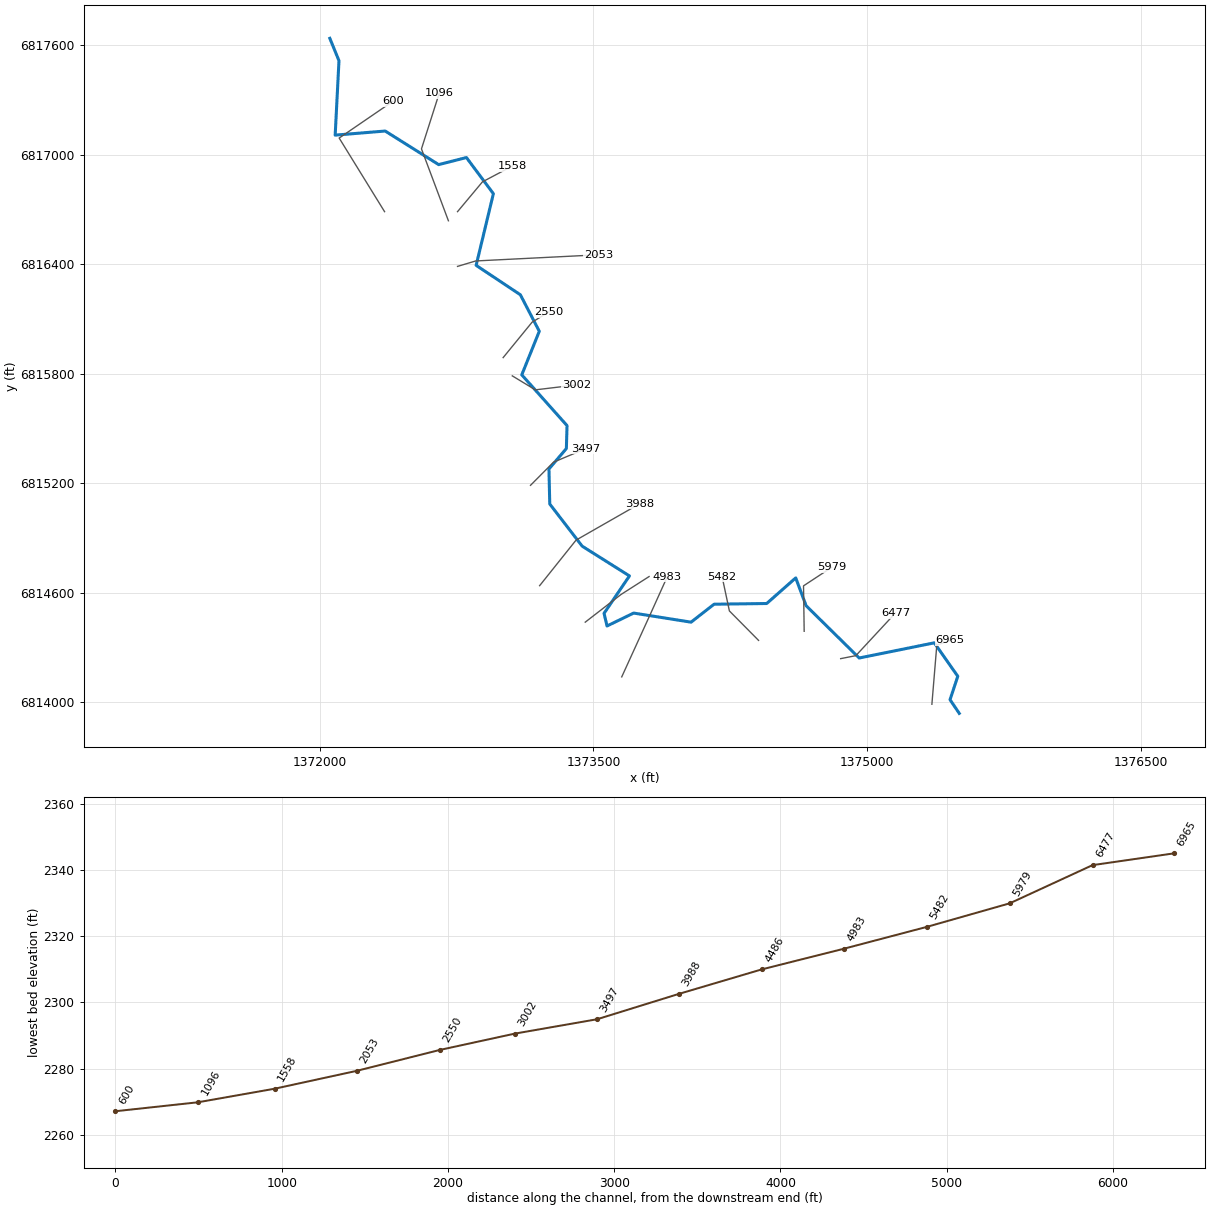
--- Sweetwater Creek Trib 10.prj (project) ---

Proj Title=Sweetwater Creek Trib 10 Base Level Engineering
Current Plan=p01
Default Exp/Contr=0.3,0.1
English Units
Geom File=g01
Flow File=f01
Plan File=p01
BEGIN DESCRIPTION:
Sweetwater Creek Trib 10
END DESCRIPTION:

--- Sweetwater Creek Trib 10.p01 (plan) ---

Plan Title=Multiple Run
Short Identifier=Multiple
Geom File=g01
Flow File=f01
Subcritical Flow
K Sum by GR= 0
Std Step Tol= 0.01
Critical Tol= 0.01
Num of Std Step Trials= 20
Max Error Tol= 0.3
Flow Tol Ratio= 0.001
Split Flow NTrial= 30
Split Flow Tol= 0.02
Split Flow Ratio= 0.02
Log Output Level= 0
Friction Slope Method= 1
Unsteady Friction Slope Method= 2
Unsteady Bridges Friction Slope Method= 1
Parabolic Critical Depth
Global Vel Dist=  1 , 1 , 1
Global Log Level= 0
CheckData=True
Encroach Param= -1, 0, 0, 0
BEGIN DESCRIPTION:
Multiple Run
END DESCRIPTION:

--- Sweetwater Creek Trib 10.f01 (steady flow) ---

Flow Title=Multiple
Number of Profiles=7
Profile Names=10-year,25-year,50-year,1pct_min,100-year,1pct_plu,500-year
River Rch & RM= Sweetwater Creek,Reach-1,6965
     361     528     673     427     852    1700    1383
River Rch & RM= Sweetwater Creek,Reach-1,5979
     446     657     842     536    1070    2135    1752
Boundary for River Rch & Prof#=Sweetwater Creek,Reach-1,1
Up Type=0
Dn Type=3
Dn Slope=0.005
Boundary for River Rch & Prof#=Sweetwater Creek,Reach-1,2
Up Type=0
Dn Type=3
Dn Slope=0.005
Boundary for River Rch & Prof#=Sweetwater Creek,Reach-1,3
Up Type=0
Dn Type=3
Dn Slope=0.005
Boundary for River Rch & Prof#=Sweetwater Creek,Reach-1,4
Up Type=0
Dn Type=3
Dn Slope=0.005
Boundary for River Rch & Prof#=Sweetwater Creek,Reach-1,5
Up Type=0
Dn Type=3
Dn Slope=0.005
Boundary for River Rch & Prof#=Sweetwater Creek,Reach-1,6
Up Type=0
Dn Type=3
Dn Slope=0.005
Boundary for River Rch & Prof#=Sweetwater Creek,Reach-1,7
Up Type=0
Dn Type=3
Dn Slope=0.005

--- Sweetwater Creek Trib 10.g01 (geometry) ---

Geom Title=Existing Conditions

River Reach=Sweetwater Creek,Reach-1
Reach XY= 30
      1375505.00      6813938.00      1375454.53      6814013.00
      1375496.96      6814141.32      1375368.34      6814324.64
      1374956.50      6814241.46      1374665.52      6814528.22
      1374608.62      6814680.53      1374449.55      6814540.18
      1374161.05      6814536.33      1374035.02      6814437.96
      1373720.22      6814487.75      1373574.42      6814416.93
      1373558.11      6814486.29      1373697.24      6814691.42
      1373438.24      6814854.45      1373260.47      6815085.55
      1373256.05      6815277.56      1373351.46      6815389.47
      1373355.22      6815515.34      1373107.07      6815793.48
      1373203.12      6816032.28      1373099.41      6816232.39
      1372856.97      6816393.68      1372951.46      6816786.53
      1372803.72      6816984.63      1372651.59      6816945.81
      1372358.32      6817129.96      1372084.33      6817107.40
      1372105.14      6817515.33      1372055.00      6817638.00

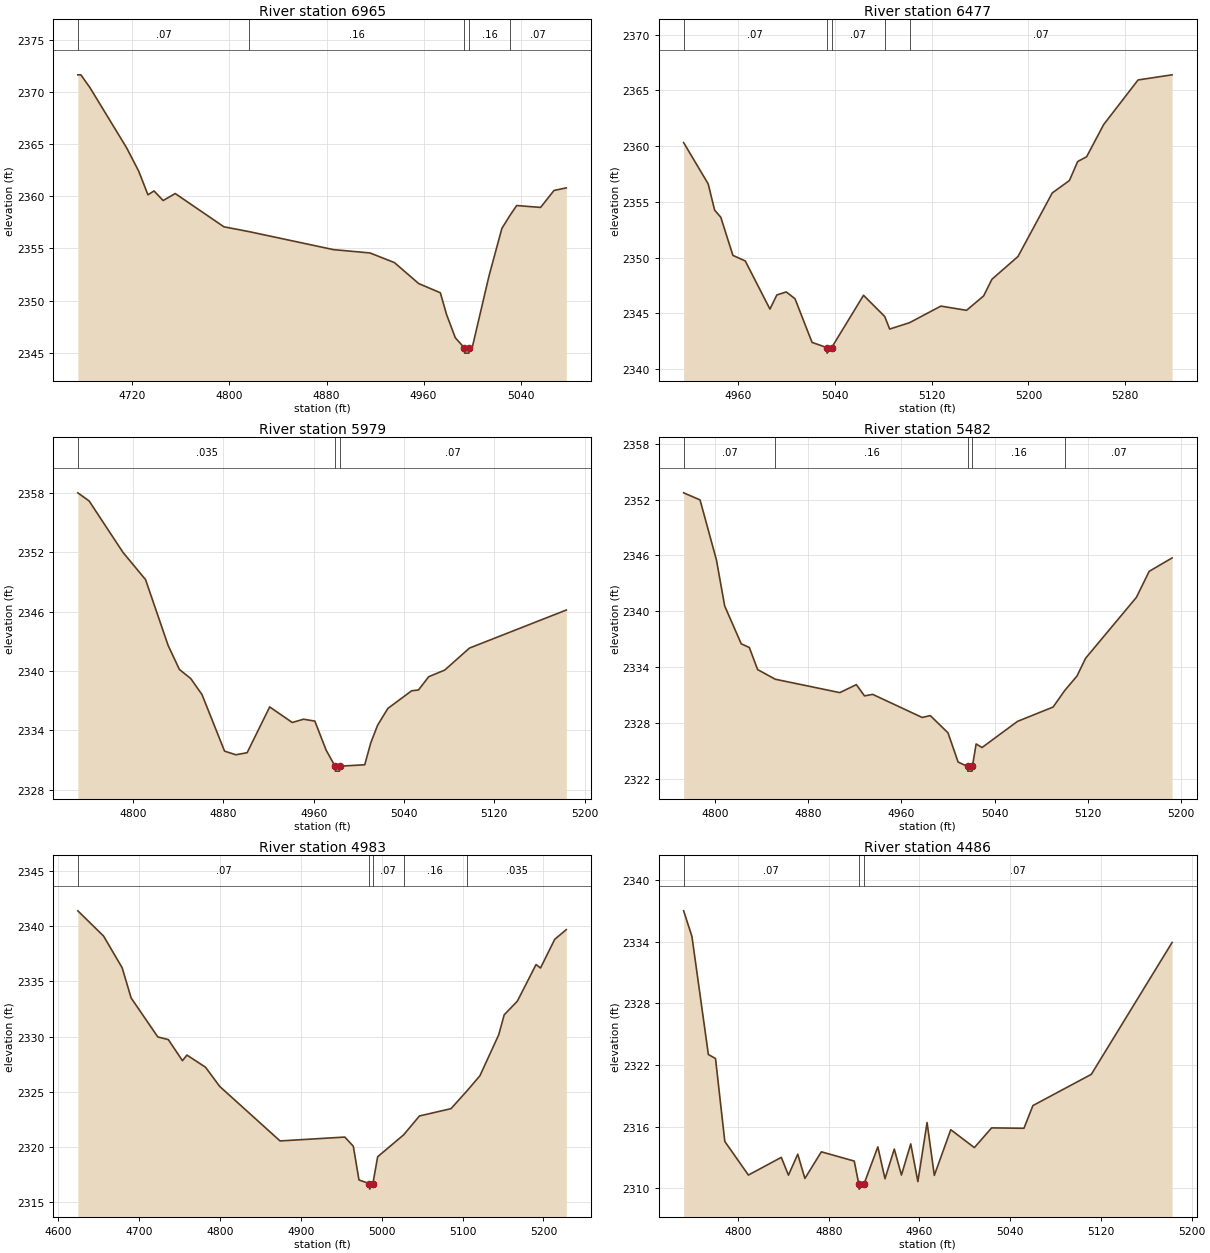
Type RM Length L Ch R = 1,6965,488,488,488
BEGIN DESCRIPTION:
Sweetwater Creek Trib 10 13.0
END DESCRIPTION:
XS GIS Cut Line= 3
      1375355.00      6813987.98      1375381.93      6814311.86
      1375455.00      6814338.00
#Sta/Elev= 30
  4675.0 2371.66  4677.5 2371.66  4685.1 2370.41  4715.2 2364.66  4725.2 2362.41
  4732.8 2360.15  4737.8 2360.52  4745.3 2359.60  4755.3 2360.27  4795.4 2357.08
  4816.0 2356.62  4885.7 2354.89  4915.8 2354.57  4935.9 2353.65  4956.0 2351.63
  4973.8 2350.75  4978.9 2348.67  4986.1 2346.44  4993.6 2345.46  4993.8 2344.96
  4997.3 2344.96  4997.6 2345.46  5000.0 2345.46  5013.9 2352.37  5024.5 2356.92
  5031.0 2358.14  5036.7 2359.12  5056.4 2358.94  5067.5 2360.57  5077.6 2360.81
#Mann=5,-1,0
  4675.0    0.07       0  4816.0    0.16       0  4993.6    0.07       0
  4997.6    0.16       0  5031.0    0.07       0
Bank Sta=4993.6,4997.6
Exp/Cntr=0.3,0.1

Type RM Length L Ch R = 1,6477,498,498,498
BEGIN DESCRIPTION:
Sweetwater Creek Trib 10 12.0
END DESCRIPTION:
XS GIS Cut Line= 3
      1374855.05      6814238.01      1374938.25      6814254.40
      1375155.02      6814488.02
#Sta/Elev= 30
  4915.2 2360.31  4935.5 2356.60  4940.8 2354.25  4945.9 2353.61  4955.9 2350.19
  4966.1 2349.69  4986.5 2345.37  4992.2 2346.64  5000.0 2346.91  5007.2 2346.30
  5021.3 2342.38  5033.5 2341.92  5033.7 2341.42  5037.5 2341.92  5063.8 2346.61
  5081.3 2344.71  5085.4 2343.58  5101.8 2344.15  5127.7 2345.64  5148.9 2345.26
  5163.0 2346.55  5169.9 2348.05  5191.4 2350.09  5219.7 2355.79  5233.9 2356.91
  5240.7 2358.61  5248.1 2359.04  5262.2 2361.93  5290.6 2365.93  5318.7 2366.39
#Mann=5,-1,0
  4915.2    0.07       0  5033.5    0.07       0  5037.5    0.07       0
  5081.3    0.16       0  5101.8    0.07       0
Bank Sta=5033.5,5037.5
Exp/Cntr=0.3,0.1

Type RM Length L Ch R = 1,5979,497,497,497
BEGIN DESCRIPTION:
Sweetwater Creek Trib 10 11.0
END DESCRIPTION:
XS GIS Cut Line= 3
      1374655.00      6814388.02      1374651.39      6814636.99
      1374804.96      6814737.97
#Sta/Elev= 30
  4751.0 2357.98  4761.0 2357.16  4791.0 2351.97  4811.0 2349.22  4831.0 2342.58
  4841.0 2340.15  4851.0 2339.24  4861.0 2337.62  4881.0 2331.91  4891.0 2331.54
  4901.0 2331.75  4921.0 2336.37  4941.0 2334.80  4951.0 2335.13  4961.0 2334.94
  4971.0 2332.01  4978.9 2330.39  4979.2 2329.89  4982.8 2329.89  4983.1 2330.39
  5005.2 2330.53  5010.6 2332.76  5016.6 2334.52  5025.7 2336.22  5046.8 2338.00
  5052.8 2338.08  5061.9 2339.42  5076.1 2340.09  5098.0 2342.31  5183.8 2346.15
#Mann=3,-1,0
  4751.0   0.035       0  4978.9    0.07       0  4983.1    0.07       0
Bank Sta=4978.9,4983.1
Exp/Cntr=0.3,0.1

Type RM Length L Ch R = 1,5482,499,499,499
BEGIN DESCRIPTION:
Sweetwater Creek Trib 10 10.0
END DESCRIPTION:
XS GIS Cut Line= 3
      1374404.99      6814338.01      1374245.07      6814499.53
      1374205.00      6814688.02
#Sta/Elev= 30
  4772.7 2352.72  4786.8 2351.96  4800.9 2345.51  4808.0 2340.56  4822.2 2336.49
  4829.2 2336.09  4836.3 2333.72  4851.5 2332.68  4907.0 2331.24  4921.2 2332.10
  4928.2 2330.89  4935.3 2331.05  4977.8 2328.57  4984.8 2328.77  5000.0 2326.92
  5008.7 2323.78  5016.8 2323.30  5017.0 2322.80  5020.7 2322.80  5021.0 2323.30
  5024.2 2325.72  5029.3 2325.34  5059.8 2328.15  5090.4 2329.69  5100.4 2331.47
  5110.9 2333.02  5118.3 2334.93  5162.0 2341.48  5173.0 2344.28  5192.7 2345.72
#Mann=5,-1,0
  4772.7    0.07       0  4851.5    0.16       0  5016.8    0.07       0
  5021.0    0.16       0  5100.4    0.07       0
Bank Sta=5016.8,5021
Exp/Cntr=0.3,0.1

Type RM Length L Ch R = 1,4983,497,497,497
BEGIN DESCRIPTION:
Sweetwater Creek Trib 10 9.0
END DESCRIPTION:
XS GIS Cut Line= 3
      1373655.01      6814138.03      1373811.03      6814479.91
      1373904.99      6814687.98
#Sta/Elev= 30
  4624.2 2341.38  4656.0 2339.10  4679.0 2336.23  4690.1 2333.50  4723.1 2329.97
  4736.1 2329.73  4753.6 2327.82  4759.1 2328.33  4782.1 2327.23  4799.7 2325.49
  4874.3 2320.56  4954.4 2320.91  4964.9 2320.08  4971.9 2317.03  4984.8 2316.70
  4985.1 2316.20  4989.1 2316.70  4995.0 2319.13  5027.1 2321.11  5046.7 2322.82
  5085.7 2323.48  5105.6 2325.10  5121.5 2326.46  5144.7 2330.16  5151.5 2331.97
  5167.8 2333.21  5190.9 2336.52  5196.4 2336.21  5214.0 2338.80  5228.3 2339.68
#Mann=5,-1,0
  4624.2    0.07       0  4984.8    0.07       0  4989.1    0.07       0
  5027.1    0.16       0  5105.6   0.035       0
Bank Sta=4984.8,4989.1
Exp/Cntr=0.3,0.1

Type RM Length L Ch R = 1,4486,498,498,498
BEGIN DESCRIPTION:
Sweetwater Creek Trib 10 8.0
END DESCRIPTION:
XS GIS Cut Line= 3
      1373454.98      6814437.99      1373651.07      6814589.65
      1373805.03      6814688.02
#Sta/Elev= 30
  4752.1 2337.00  4759.4 2334.52  4773.9 2323.02  4780.2 2322.63  4788.4 2314.56
  4809.2 2311.29  4838.2 2313.01  4844.5 2311.28  4852.7 2313.32  4859.0 2310.96
  4873.5 2313.55  4902.5 2312.65  4906.5 2310.42  4906.8 2309.92  4911.1 2310.42
  4923.3 2314.03  4929.6 2310.93  4937.8 2313.82  4944.1 2311.29  4952.3 2314.32
  4958.6 2310.65  4966.7 2316.40  4973.1 2311.26  4987.6 2315.70  5008.4 2313.96
  5023.6 2315.88  5052.1 2315.84  5060.0 2318.05  5111.5 2321.09  5182.7 2333.92
#Mann=3,-1,0
  4752.1    0.07       0  4906.5    0.07       0  4911.1    0.07       0
Bank Sta=4906.5,4911.1
Exp/Cntr=0.3,0.1

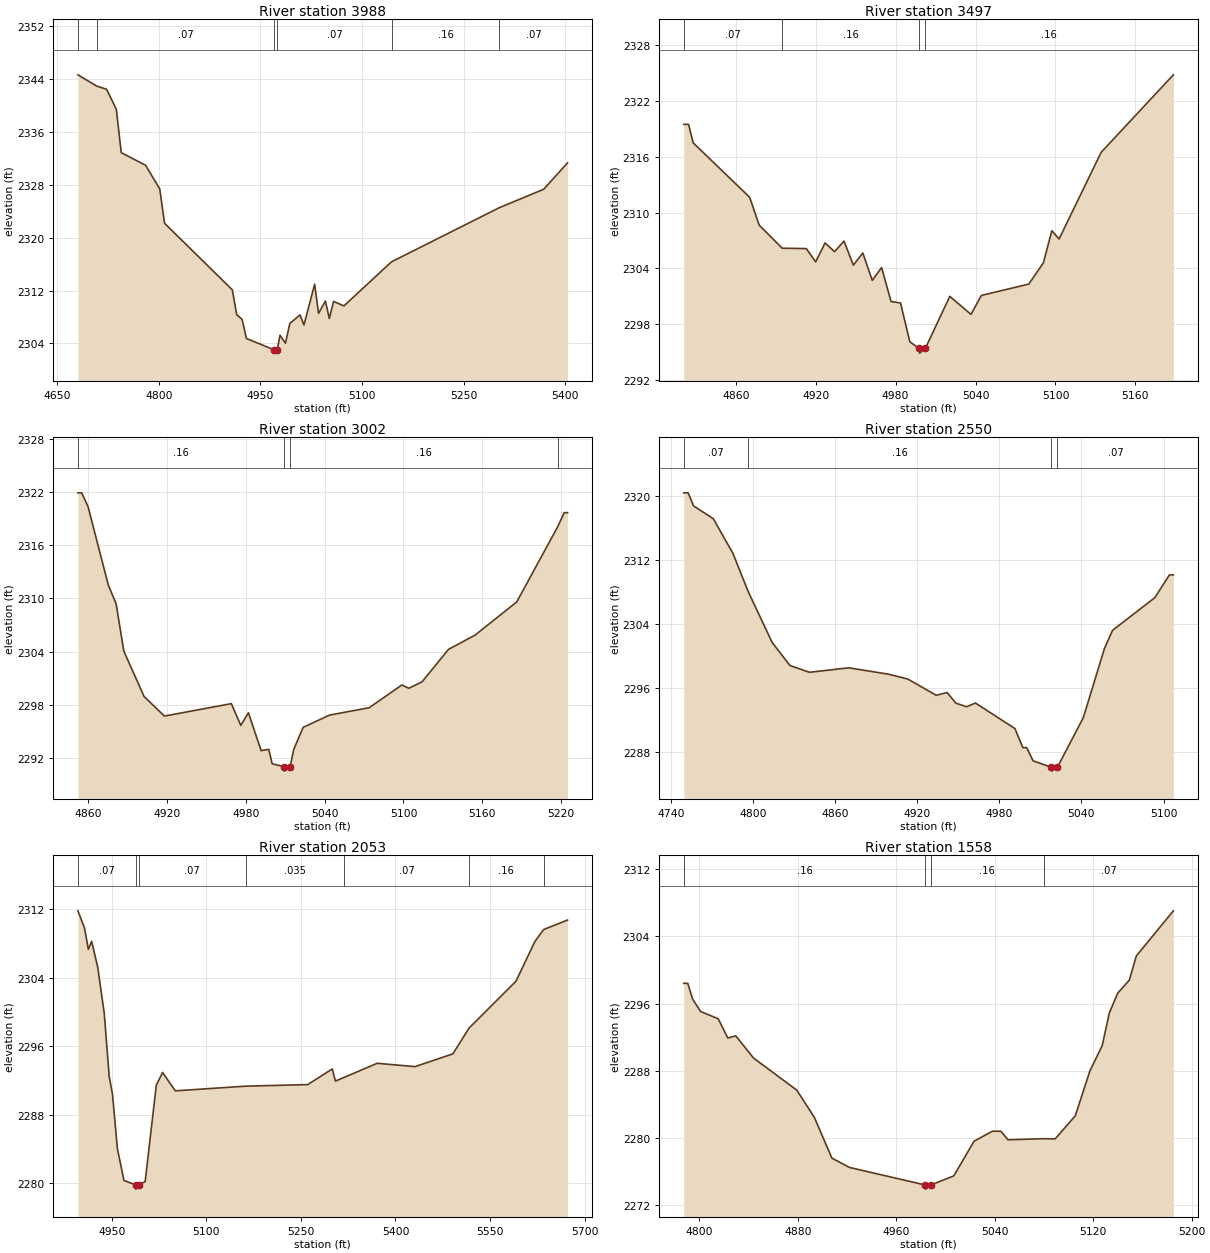
Type RM Length L Ch R = 1,3988,491,491,491
BEGIN DESCRIPTION:
Sweetwater Creek Trib 10 7.0
END DESCRIPTION:
XS GIS Cut Line= 3
      1373205.00      6814638.00      1373404.69      6814887.67
      1373754.96      6815087.98
#Sta/Elev= 30
  4680.3 2344.62  4708.1 2342.92  4722.7 2342.43  4737.1 2339.40  4744.3 2332.85
  4780.3 2330.94  4801.2 2327.36  4808.3 2322.17  4908.4 2312.10  4914.8 2308.36
  4922.8 2307.63  4929.2 2304.75  4970.1 2303.03  4970.5 2302.53  4974.7 2303.03
  4978.8 2305.23  4986.9 2304.03  4993.3 2307.01  5008.4 2308.31  5014.2 2306.79
  5030.0 2312.95  5035.8 2308.54  5045.9 2310.41  5051.6 2307.78  5058.0 2310.35
  5073.2 2309.67  5143.5 2316.34  5302.8 2324.53  5368.3 2327.31  5403.5 2331.31
#Mann=6,-1,0
  4680.3   0.035       0  4708.1    0.07       0  4970.1    0.07       0
  4974.7    0.07       0  5143.5    0.16       0  5302.8    0.07       0
Bank Sta=4970.1,4974.7
Exp/Cntr=0.3,0.1

Type RM Length L Ch R = 1,3497,495,495,495
BEGIN DESCRIPTION:
Sweetwater Creek Trib 10 6.0
END DESCRIPTION:
XS GIS Cut Line= 3
      1373154.97      6815187.97      1373281.23      6815314.85
      1373454.97      6815387.99
#Sta/Elev= 30
  4821.0 2319.51  4824.6 2319.51  4828.1 2317.52  4870.5 2311.66  4877.6 2308.67
  4894.9 2306.18  4913.0 2306.14  4920.0 2304.71  4927.1 2306.75  4934.2 2305.81
  4941.3 2306.95  4948.3 2304.36  4955.4 2305.67  4962.5 2302.72  4969.5 2304.10
  4976.6 2300.44  4983.7 2300.29  4990.7 2296.11  4997.7 2295.39  4998.0 2294.89
  5002.3 2295.39  5020.7 2301.00  5036.6 2299.06  5044.4 2301.10  5080.0 2302.32
  5090.9 2304.60  5097.3 2308.06  5102.7 2307.17  5134.3 2316.50  5188.5 2324.84
#Mann=4,-1,0
  4821.0    0.07       0  4894.9    0.16       0  4997.7    0.07       0
  5002.3    0.16       0
Bank Sta=4997.7,5002.3
Exp/Cntr=0.3,0.1

Type RM Length L Ch R = 1,3002,452,452,452
BEGIN DESCRIPTION:
Sweetwater Creek Trib 10 5.0
END DESCRIPTION:
XS GIS Cut Line= 3
      1373055.02      6815787.99      1373181.61      6815711.31
      1373405.02      6815738.00
#Sta/Elev= 30
  4852.0 2321.89  4854.9 2321.89  4859.7 2320.35  4875.2 2311.49  4881.1 2309.40
  4887.0 2304.06  4902.4 2298.96  4917.9 2296.75  4968.9 2298.15  4976.1 2295.70
  4981.9 2297.12  4991.6 2292.86  4997.4 2293.00  5000.0 2291.38  5009.0 2291.05
  5009.3 2290.55  5013.7 2291.05  5016.4 2292.98  5023.6 2295.48  5043.7 2296.86
  5073.9 2297.69  5098.8 2300.25  5104.1 2299.88  5114.2 2300.61  5134.3 2304.26
  5154.5 2305.86  5186.3 2309.60  5217.5 2318.07  5222.5 2319.66  5225.0 2319.66
#Mann=4,-1,0
  4852.0    0.16       0  5009.0    0.07       0  5013.7    0.16       0
  5217.5    0.07       0
Bank Sta=5009,5013.7
Exp/Cntr=0.3,0.1

Type RM Length L Ch R = 1,2550,497,497,497
BEGIN DESCRIPTION:
Sweetwater Creek Trib 10 4.0
END DESCRIPTION:
XS GIS Cut Line= 3
      1373004.99      6815887.98      1373163.52      6816082.06
      1373254.98      6816137.99
#Sta/Elev= 30
  4749.4 2320.36  4752.6 2320.36  4756.6 2318.73  4771.0 2317.13  4785.3 2312.82
  4796.6 2307.99  4814.0 2301.68  4827.0 2298.80  4841.3 2297.95  4870.0 2298.51
  4898.8 2297.72  4913.1 2297.11  4933.9 2295.08  4941.8 2295.42  4948.3 2294.10
  4956.0 2293.65  4962.6 2294.11  4991.4 2290.93  4997.2 2288.55  5000.0 2288.55
  5004.7 2286.90  5017.8 2286.11  5018.1 2285.61  5022.5 2286.11  5041.4 2292.29
  5056.9 2300.96  5062.8 2303.20  5093.6 2307.26  5104.3 2310.11  5107.2 2310.11
#Mann=4,-1,0
  4749.4    0.07       0  4796.6    0.16       0  5017.8    0.07       0
  5022.5    0.07       0
Bank Sta=5017.8,5022.5
Exp/Cntr=0.3,0.1

Type RM Length L Ch R = 1,2053,495,495,495
BEGIN DESCRIPTION:
Sweetwater Creek Trib 10 3.0
END DESCRIPTION:
XS GIS Cut Line= 3
      1372754.96      6816387.99      1372854.51      6816417.77
      1373526.66      6816451.54
#Sta/Elev= 30
  4896.1 2311.84  4906.6 2309.84  4912.7 2307.34  4917.9 2308.28  4927.5 2305.28
  4937.9 2299.88  4945.8 2292.48  4951.0 2290.41  4958.8 2284.04  4969.2 2280.34
  4987.7 2279.83  4988.1 2279.33  4992.4 2279.83  5002.8 2280.20  5020.5 2291.47
  5030.5 2292.96  5050.6 2290.81  5162.5 2291.36  5260.8 2291.54  5299.7 2293.37
  5304.7 2291.95  5318.7 2292.39  5371.0 2294.03  5431.0 2293.64  5491.1 2295.13
  5516.6 2298.13  5591.2 2303.62  5621.3 2308.27  5635.2 2309.66  5673.0 2310.76
#Mann=7,-1,0
  4896.1    0.07       0  4987.7    0.07       0  4992.4    0.07       0
  5162.5   0.035       0  5318.7    0.07       0  5516.6    0.16       0
  5635.2    0.07       0
Bank Sta=4987.7,4992.4
Exp/Cntr=0.3,0.1

Type RM Length L Ch R = 1,1558,462,462,462
BEGIN DESCRIPTION:
Sweetwater Creek Trib 10 2.0
END DESCRIPTION:
XS GIS Cut Line= 3
      1372754.97      6816687.96      1372891.44      6816851.24
      1373054.96      6816937.98
#Sta/Elev= 30
  4787.2 2298.41  4790.5 2298.41  4794.4 2296.55  4800.9 2295.06  4815.2 2294.20
  4823.0 2291.91  4829.5 2292.16  4843.9 2289.52  4879.0 2285.71  4893.3 2282.48
  4907.6 2277.61  4921.9 2276.50  4983.3 2274.42  4983.6 2273.92  4988.2 2274.42
  5006.7 2275.50  5023.1 2279.62  5038.0 2280.81  5045.0 2280.81  5050.7 2279.79
  5079.6 2279.92  5089.0 2279.90  5105.4 2282.64  5117.2 2287.96  5127.3 2291.02
  5133.0 2294.86  5139.9 2297.25  5149.3 2298.79  5155.0 2301.67  5185.1 2307.04
#Mann=4,-1,0
  4787.2    0.16       0  4983.3    0.07       0  4988.2    0.16       0
  5079.6    0.07       0
Bank Sta=4983.3,4988.2
Exp/Cntr=0.3,0.1

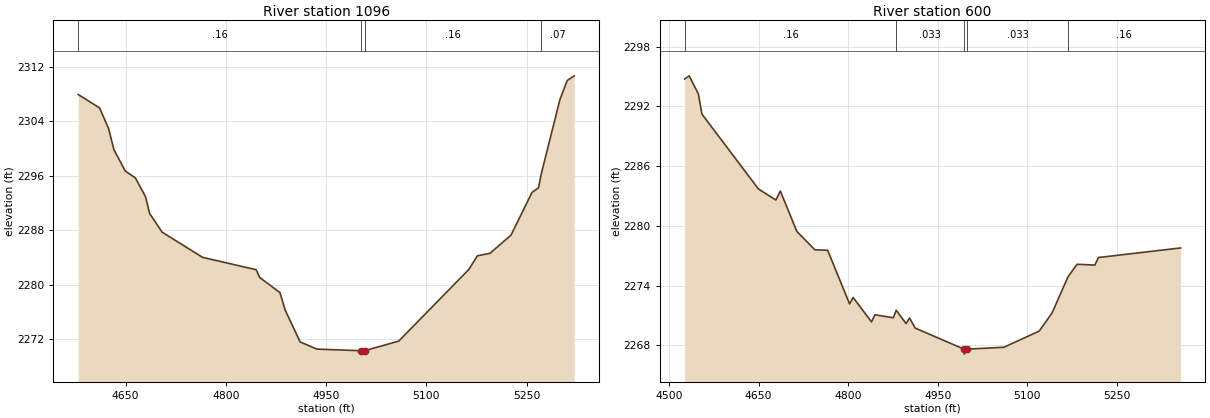
Type RM Length L Ch R = 1,1096,496,496,496
BEGIN DESCRIPTION:
Sweetwater Creek Trib 10 1.0
END DESCRIPTION:
XS GIS Cut Line= 3
      1372705.00      6816638.00      1372557.30      6817032.14
      1372655.00      6817338.01
#Sta/Elev= 30
  4579.1 2307.92  4611.1 2305.95  4624.5 2302.93  4632.5 2299.83  4649.4 2296.70
  4664.5 2295.69  4679.7 2292.95  4685.9 2290.47  4704.6 2287.72  4765.2 2284.02
  4845.3 2282.21  4850.6 2281.07  4880.9 2278.85  4888.8 2276.27  4911.1 2271.61
  4936.1 2270.56  5002.4 2270.32  5002.7 2269.82  5007.4 2270.32  5058.6 2271.73
  5163.6 2282.26  5176.3 2284.25  5195.1 2284.61  5226.6 2287.29  5258.1 2293.57
  5267.6 2294.21  5271.7 2296.22  5299.7 2307.17  5310.6 2309.97  5321.1 2310.66
#Mann=4,-1,0
  4579.1    0.16       0  5002.4    0.07       0  5007.4    0.16       0
  5271.7    0.07       0
Bank Sta=5002.4,5007.4
Exp/Cntr=0.3,0.1

Type RM Length L Ch R = 1,600,0,0,0
BEGIN DESCRIPTION:
Sweetwater Creek Trib 10 0.1
END DESCRIPTION:
XS GIS Cut Line= 3
      1372355.01      6816687.98      1372106.22      6817091.43
      1372400.44      6817292.75
#Sta/Elev= 30
  4526.0 2294.74  4533.7 2295.06  4549.1 2293.23  4555.0 2291.22  4649.6 2283.70
  4678.8 2282.59  4686.3 2283.49  4714.0 2279.43  4744.2 2277.59  4765.5 2277.55
  4802.2 2272.16  4808.1 2272.81  4838.9 2270.36  4844.7 2271.07  4875.5 2270.77
  4880.3 2271.53  4896.8 2270.19  4902.7 2270.74  4912.2 2269.73  4993.9 2267.62
  4994.2 2267.12  4998.9 2267.62  5060.5 2267.81  5119.7 2269.43  5141.2 2271.25
  5168.0 2274.89  5183.1 2276.14  5212.9 2276.06  5219.0 2276.82  5356.5 2277.78
#Mann=5,-1,0
  4526.0    0.16       0  4880.3   0.033       0  4993.9   0.033       0
  4998.9   0.033       0  5168.0    0.16       0
Bank Sta=4993.9,4998.9
Exp/Cntr=0.3,0.1

Chan Stop Cuts=-1