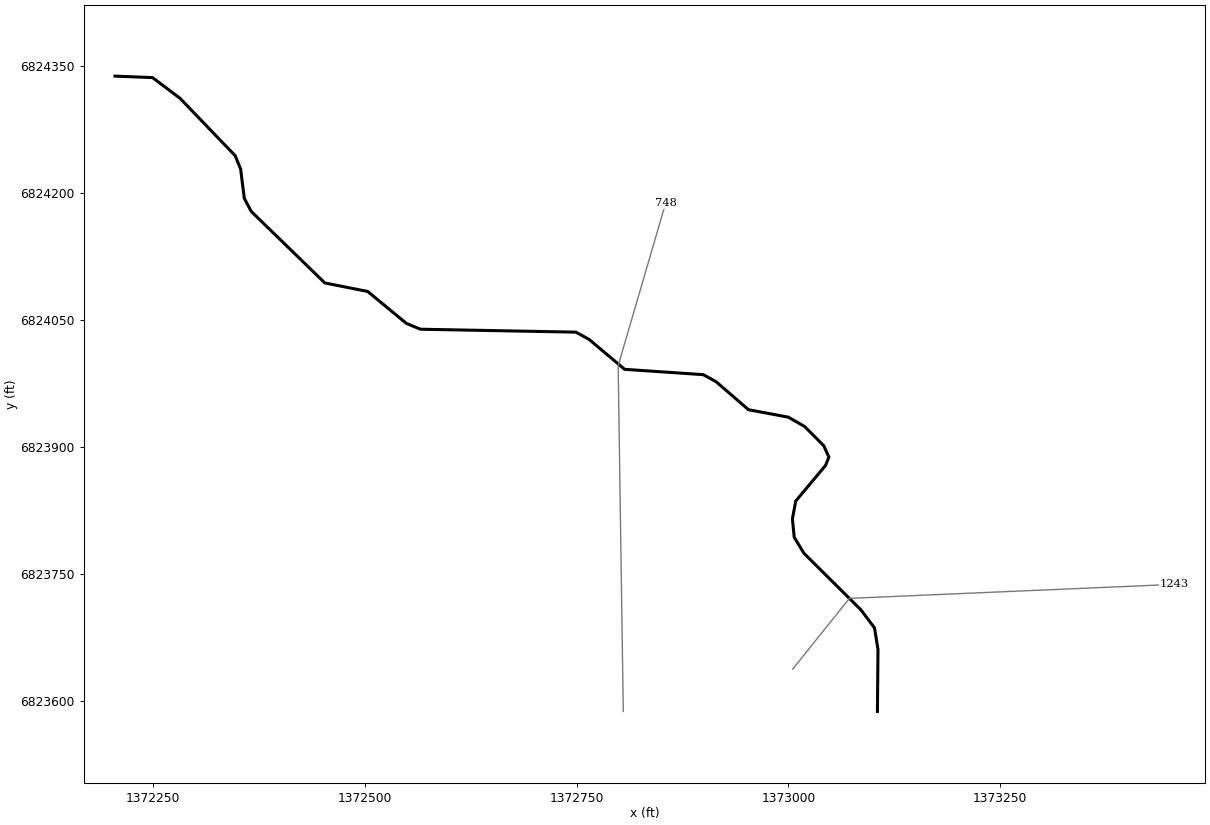
--- Sweetwater Creek Trib 11.prj (project) ---

Proj Title=Sweetwater Creek Trib 11 Base Level Engineering
Current Plan=p01
Default Exp/Contr=0.3,0.1
English Units
Geom File=g01
Flow File=f01
Plan File=p01
BEGIN DESCRIPTION:
Sweetwater Creek Trib 11
END DESCRIPTION:

--- Sweetwater Creek Trib 11.p01 (plan) ---

Plan Title=Multiple Run
Short Identifier=Multiple
Geom File=g01
Flow File=f01
Subcritical Flow
K Sum by GR= 0
Std Step Tol= 0.01
Critical Tol= 0.01
Num of Std Step Trials= 20
Max Error Tol= 0.3
Flow Tol Ratio= 0.001
Split Flow NTrial= 30
Split Flow Tol= 0.02
Split Flow Ratio= 0.02
Log Output Level= 0
Friction Slope Method= 1
Unsteady Friction Slope Method= 2
Unsteady Bridges Friction Slope Method= 1
Parabolic Critical Depth
Global Vel Dist=  1 , 1 , 1
Global Log Level= 0
CheckData=True
Encroach Param= -1, 0, 0, 0
BEGIN DESCRIPTION:
Multiple Run
END DESCRIPTION:

--- Sweetwater Creek Trib 11.f01 (steady flow) ---

Flow Title=Multiple
Number of Profiles=7
Profile Names=10-year,25-year,50-year,1pct_min,100-year,1pct_plu,500-year
River Rch & RM= Sweetwater Creek,Reach-1,1243
     388     566     721     456     911    1817    1474
Boundary for River Rch & Prof#=Sweetwater Creek,Reach-1,1
Up Type=0
Dn Type=3
Dn Slope=0.005
Boundary for River Rch & Prof#=Sweetwater Creek,Reach-1,2
Up Type=0
Dn Type=3
Dn Slope=0.005
Boundary for River Rch & Prof#=Sweetwater Creek,Reach-1,3
Up Type=0
Dn Type=3
Dn Slope=0.005
Boundary for River Rch & Prof#=Sweetwater Creek,Reach-1,4
Up Type=0
Dn Type=3
Dn Slope=0.005
Boundary for River Rch & Prof#=Sweetwater Creek,Reach-1,5
Up Type=0
Dn Type=3
Dn Slope=0.005
Boundary for River Rch & Prof#=Sweetwater Creek,Reach-1,6
Up Type=0
Dn Type=3
Dn Slope=0.005
Boundary for River Rch & Prof#=Sweetwater Creek,Reach-1,7
Up Type=0
Dn Type=3
Dn Slope=0.005

--- Sweetwater Creek Trib 11.g01 (geometry) ---

Geom Title=Existing Conditions

River Reach=Sweetwater Creek,Reach-1
Reach XY= 30
      1373105.00      6823588.00      1373105.67      6823661.00
      1373101.60      6823686.59      1373085.33      6823708.14
      1373018.16      6823774.80      1373006.78      6823793.65
      1373004.64      6823815.21      1373008.59      6823836.36
      1373043.67      6823878.26      1373047.74      6823888.30
      1373041.60      6823901.73      1373019.03      6823924.39
      1372999.78      6823935.40      1372952.88      6823944.14
      1372914.66      6823977.16      1372899.44      6823985.56
      1372806.60      6823991.86      1372764.65      6824027.15
      1372749.06      6824035.74      1372565.50      6824039.20
      1372548.92      6824046.09      1372503.25      6824083.78
      1372452.69      6824093.82      1372365.77      6824178.30
      1372357.64      6824193.63      1372353.30      6824228.21
      1372346.85      6824244.06      1372281.87      6824311.68
      1372249.35      6824336.21      1372205.00      6824338.00

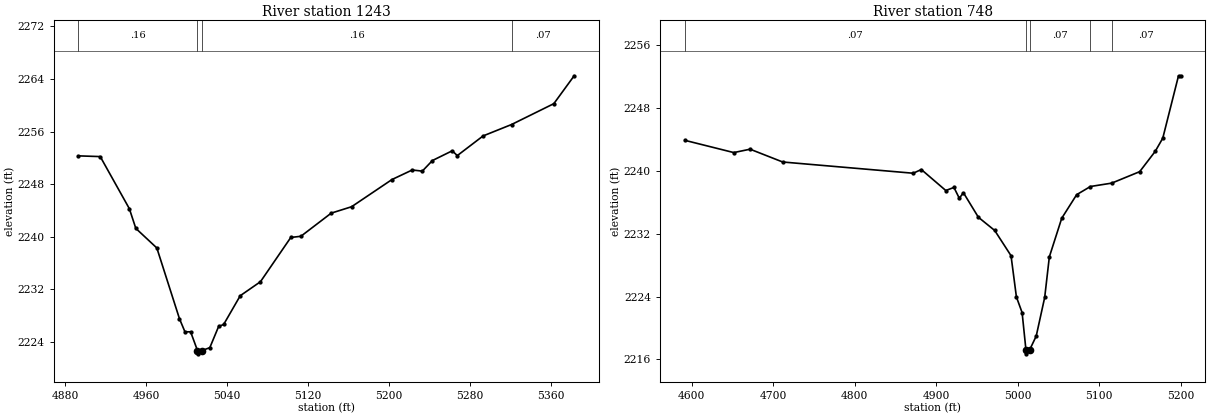
Type RM Length L Ch R = 1,1243,495,495,495
BEGIN DESCRIPTION:
Sweetwater Creek Trib 11 1.0
END DESCRIPTION:
XS GIS Cut Line= 3
      1373005.02      6823638.03      1373071.99      6823721.48
      1373455.04      6823738.00
#Sta/Elev= 30
  4893.0 2252.31  4914.6 2252.20  4943.4 2244.28  4949.8 2241.28  4970.6 2238.30
  4993.0 2227.53  4998.4 2225.55  5004.0 2225.55  5010.8 2222.70  5011.1 2222.20
  5015.2 2222.70  5023.0 2223.14  5031.7 2226.36  5036.7 2226.67  5053.1 2231.04
  5073.1 2233.17  5103.1 2239.90  5113.1 2240.08  5143.1 2243.60  5163.2 2244.57
  5203.2 2248.71  5223.2 2250.16  5233.2 2249.99  5243.2 2251.60  5262.8 2253.08
  5267.8 2252.35  5293.3 2255.34  5321.5 2257.08  5363.3 2260.25  5383.4 2264.49
#Mann=4,-1,0
  4893.0    0.16       0  5010.8    0.07       0  5015.2    0.16       0
  5321.5    0.07       0
Bank Sta=5010.8,5015.2
Exp/Cntr=0.3,0.1

Type RM Length L Ch R = 1,748,0,0,0
BEGIN DESCRIPTION:
Sweetwater Creek Trib 11 0.1
END DESCRIPTION:
XS GIS Cut Line= 3
      1372805.00      6823588.04      1372798.97      6823996.19
      1372854.99      6824187.98
#Sta/Elev= 30
  4591.8 2243.91  4651.8 2242.35  4671.8 2242.78  4711.8 2241.15  4871.8 2239.72
  4881.8 2240.19  4911.8 2237.52  4921.8 2237.91  4928.4 2236.53  4933.4 2237.24
  4951.8 2234.11  4971.8 2232.43  4991.8 2229.22  4998.4 2223.97  5005.4 2221.97
  5010.1 2217.22  5010.4 2216.72  5014.6 2217.22  5022.7 2218.98  5033.1 2223.91
  5038.8 2229.07  5054.0 2233.99  5072.3 2236.99  5089.2 2238.03  5115.3 2238.46
  5149.6 2239.92  5168.6 2242.50  5177.9 2244.18  5197.2 2252.13  5199.8 2252.13
#Mann=5,-1,0
  4591.8    0.07       0  5010.1    0.07       0  5014.6    0.07       0
  5089.2    0.16       0  5115.3    0.07       0
Bank Sta=5010.1,5014.6
Exp/Cntr=0.3,0.1

Chan Stop Cuts=-1