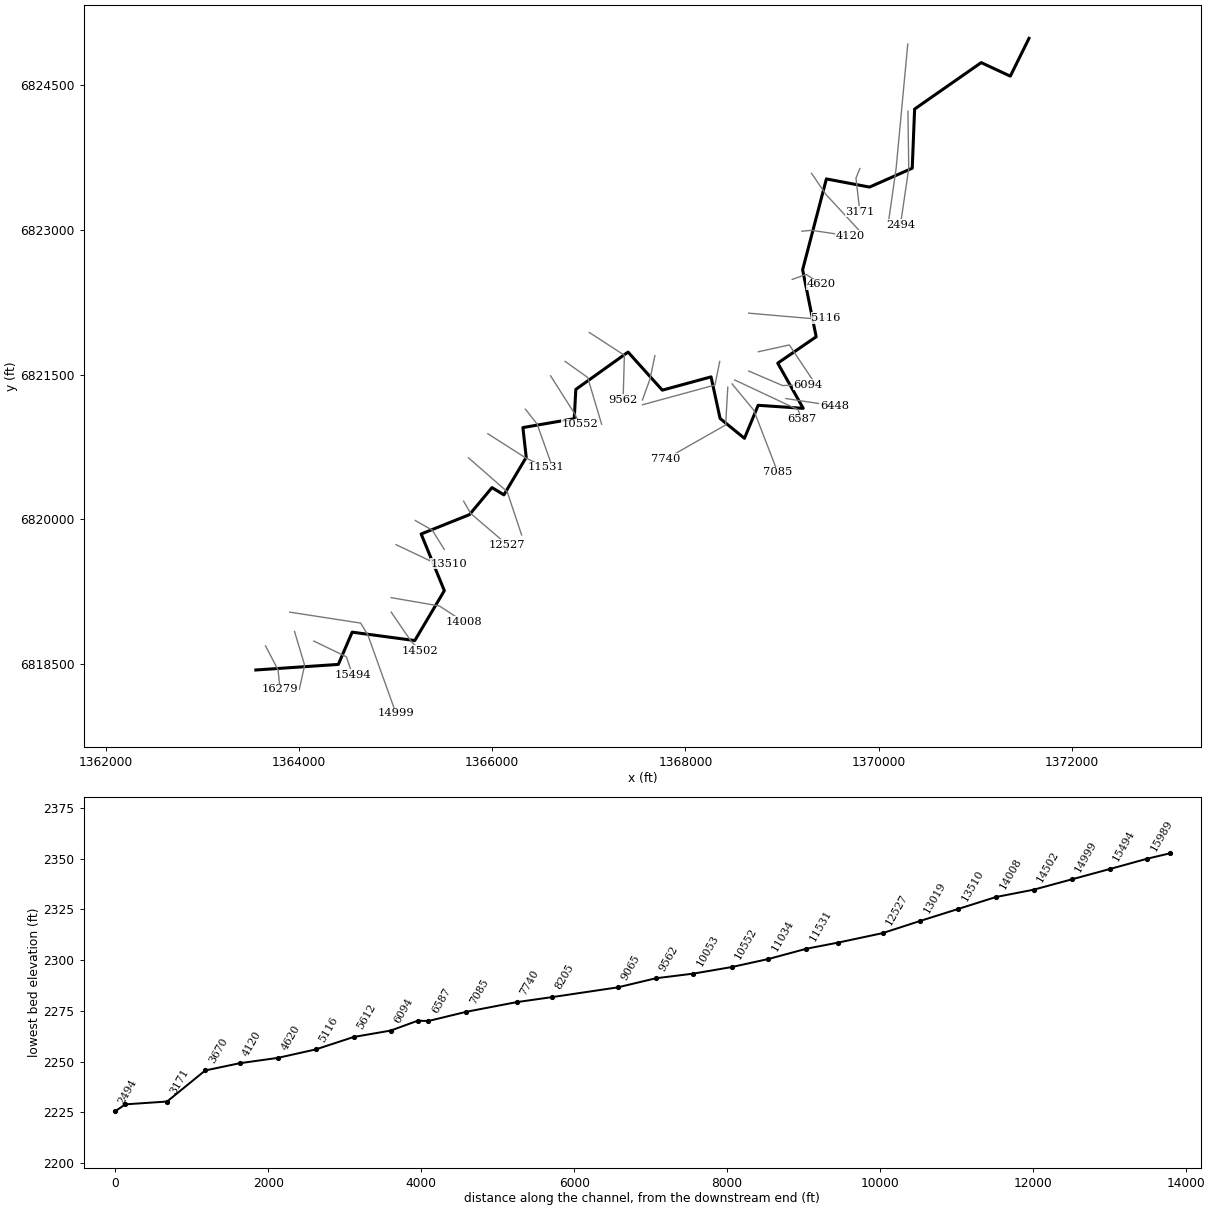
--- Sweetwater Creek Trib 12.prj (project) ---

Proj Title=Sweetwater Creek Trib 12 Base Level Engineering
Current Plan=p01
Default Exp/Contr=0.3,0.1
English Units
Geom File=g01
Flow File=f01
Plan File=p01
BEGIN DESCRIPTION:
Sweetwater Creek Trib 12
END DESCRIPTION:

--- Sweetwater Creek Trib 12.p01 (plan) ---

Plan Title=Multiple Run
Short Identifier=Multiple
Geom File=g01
Flow File=f01
Subcritical Flow
K Sum by GR= 0
Std Step Tol= 0.01
Critical Tol= 0.01
Num of Std Step Trials= 20
Max Error Tol= 0.3
Flow Tol Ratio= 0.001
Split Flow NTrial= 30
Split Flow Tol= 0.02
Split Flow Ratio= 0.02
Log Output Level= 0
Friction Slope Method= 1
Unsteady Friction Slope Method= 2
Unsteady Bridges Friction Slope Method= 1
Parabolic Critical Depth
Global Vel Dist=  1 , 1 , 1
Global Log Level= 0
CheckData=True
Encroach Param= -1, 0, 0, 0
BEGIN DESCRIPTION:
Multiple Run
END DESCRIPTION:

--- Sweetwater Creek Trib 12.f01 (steady flow) ---

Flow Title=Multiple
Number of Profiles=7
Profile Names=10-year,25-year,50-year,1pct_min,100-year,1pct_plu,500-year
River Rch & RM= Sweetwater Creek,Reach-1,16279
     460     676     864     548    1094    2183    1779
River Rch & RM= Sweetwater Creek,Reach-1,10053
     608     904    1164     744    1485    2963    2451
River Rch & RM= Sweetwater Creek,Reach-1,5612
     647     963    1242     795    1586    3164    2622
Boundary for River Rch & Prof#=Sweetwater Creek,Reach-1,1
Up Type=0
Dn Type=3
Dn Slope=0.005
Boundary for River Rch & Prof#=Sweetwater Creek,Reach-1,2
Up Type=0
Dn Type=3
Dn Slope=0.005
Boundary for River Rch & Prof#=Sweetwater Creek,Reach-1,3
Up Type=0
Dn Type=3
Dn Slope=0.005
Boundary for River Rch & Prof#=Sweetwater Creek,Reach-1,4
Up Type=0
Dn Type=3
Dn Slope=0.005
Boundary for River Rch & Prof#=Sweetwater Creek,Reach-1,5
Up Type=0
Dn Type=3
Dn Slope=0.005
Boundary for River Rch & Prof#=Sweetwater Creek,Reach-1,6
Up Type=0
Dn Type=3
Dn Slope=0.005
Boundary for River Rch & Prof#=Sweetwater Creek,Reach-1,7
Up Type=0
Dn Type=3
Dn Slope=0.005

--- Sweetwater Creek Trib 12.g01 (geometry) ---

Geom Title=Existing Conditions

River Reach=Sweetwater Creek,Reach-1
Reach XY= 30
      1363555.00      6818438.00      1364408.44      6818495.79
      1364551.57      6818830.21      1365199.59      6818743.16
      1365505.29      6819260.77      1365265.28      6819848.16
      1365765.37      6820048.98      1365998.07      6820329.10
      1366121.70      6820254.19      1366352.63      6820643.53
      1366317.95      6820951.64      1366849.44      6821043.62
      1366865.75      6821347.68      1367406.26      6821734.56
      1367760.62      6821339.73      1368265.05      6821477.41
      1368358.57      6821046.15      1368610.65      6820840.22
      1368752.26      6821182.66      1369218.75      6821151.20
      1368955.09      6821619.78      1369352.92      6821893.23
      1369212.56      6822588.00      1369458.47      6823530.19
      1369904.97      6823445.49      1370346.72      6823641.06
      1370371.43      6824254.76      1371060.63      6824736.31
      1371361.50      6824595.62      1371555.00      6824988.00

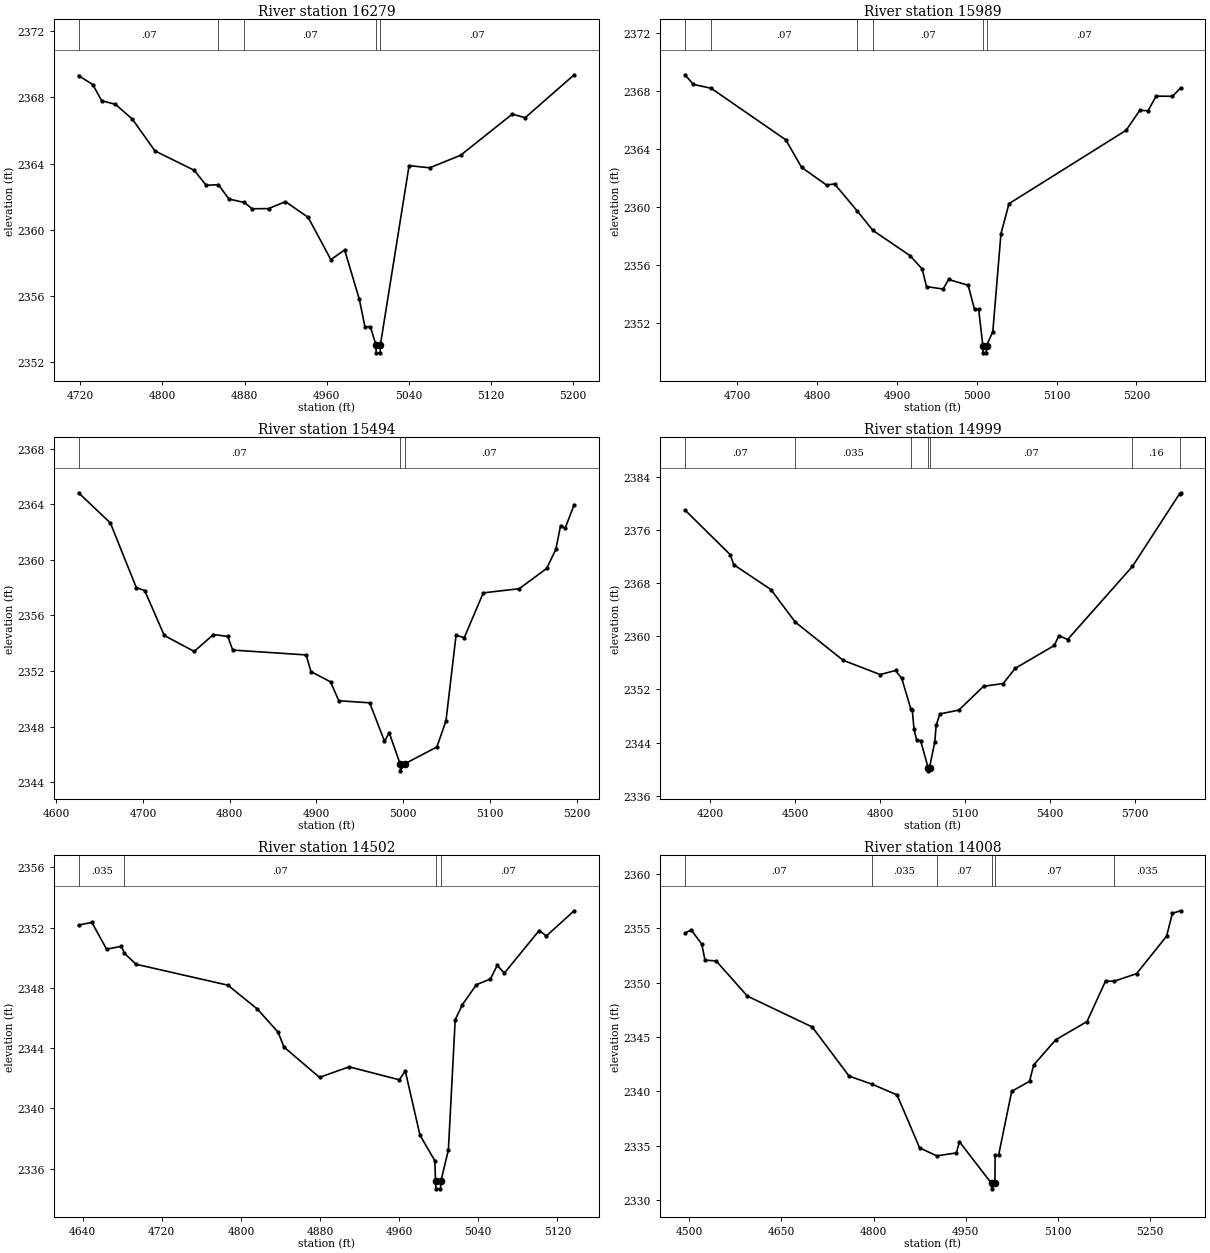
Type RM Length L Ch R = 1,16279,290,290,290
BEGIN DESCRIPTION:
Sweetwater Creek Trib 12 30.0
END DESCRIPTION:
XS GIS Cut Line= 3
      1363655.01      6818687.99      1363785.01      6818437.97
      1363805.00      6818237.96
#Sta/Elev= 30
  4718.2 2369.32  4732.1 2368.78  4740.7 2367.80  4754.2 2367.58  4770.6 2366.69
  4792.7 2364.76  4830.9 2363.59  4842.6 2362.68  4854.5 2362.72  4864.7 2361.85
  4879.7 2361.64  4887.3 2361.26  4903.3 2361.27  4919.8 2361.69  4941.9 2360.74
  4964.0 2358.18  4977.4 2358.77  4991.7 2355.79  4997.2 2354.12  5002.5 2354.12
  5007.8 2353.04  5008.1 2352.54  5012.0 2352.54  5012.3 2353.04  5040.2 2363.87
  5060.3 2363.74  5090.4 2364.50  5140.7 2366.99  5153.2 2366.77  5201.0 2369.37
#Mann=5,-1,0
  4718.2    0.07       0  4854.5    0.16       0  4879.7    0.07       0
  5007.8    0.07       0  5012.3    0.07       0
Bank Sta=5007.8,5012.3
Exp/Cntr=0.3,0.1

Type RM Length L Ch R = 1,15989,495,495,495
BEGIN DESCRIPTION:
Sweetwater Creek Trib 12 29.0
END DESCRIPTION:
XS GIS Cut Line= 3
      1363955.00      6818838.02      1364059.70      6818487.63
      1364005.01      6818238.05
#Sta/Elev= 30
  4634.3 2369.09  4644.8 2368.43  4667.1 2368.16  4760.7 2364.61  4780.4 2362.72
  4811.7 2361.50  4821.7 2361.58  4850.1 2359.72  4869.8 2358.38  4916.1 2356.65
  4931.5 2355.73  4937.0 2354.51  4957.9 2354.34  4964.6 2355.00  4989.2 2354.60
  4997.2 2352.94  5002.4 2352.94  5007.6 2350.45  5007.9 2349.95  5011.8 2349.95
  5012.2 2350.45  5020.1 2351.40  5030.3 2358.15  5040.4 2360.22  5187.2 2365.27
  5204.4 2366.65  5214.6 2366.61  5224.8 2367.62  5245.3 2367.61  5255.5 2368.18
#Mann=6,-1,0
  4634.3   0.035       0  4667.1    0.07       0  4850.1    0.16       0
  4869.8    0.07       0  5007.6    0.07       0  5012.2    0.07       0
Bank Sta=5007.6,5012.2
Exp/Cntr=0.3,0.1

Type RM Length L Ch R = 1,15494,495,495,495
BEGIN DESCRIPTION:
Sweetwater Creek Trib 12 28.0
END DESCRIPTION:
XS GIS Cut Line= 3
      1364154.96      6818738.02      1364491.88      6818574.73
      1364555.00      6818388.01
#Sta/Elev= 30
  4625.6 2364.84  4662.3 2362.67  4692.3 2358.00  4701.9 2357.80  4724.5 2354.56
  4759.0 2353.41  4781.2 2354.63  4797.7 2354.49  4803.4 2353.51  4888.1 2353.16
  4893.6 2351.96  4916.2 2351.22  4925.7 2349.86  4961.3 2349.71  4978.4 2346.95
  4983.9 2347.55  4996.4 2345.31  4996.8 2344.81  5001.6 2345.31  5038.8 2346.53
  5049.3 2348.41  5060.9 2354.57  5070.4 2354.41  5092.3 2357.63  5133.8 2357.93
  5165.4 2359.39  5176.0 2360.77  5181.4 2362.47  5186.7 2362.29  5197.1 2363.98
#Mann=3,-1,0
  4625.6    0.07       0  4996.4    0.07       0  5001.6    0.07       0
Bank Sta=4996.4,5001.6
Exp/Cntr=0.3,0.1

Type RM Length L Ch R = 1,14999,497,497,497
BEGIN DESCRIPTION:
Sweetwater Creek Trib 12 27.0
END DESCRIPTION:
XS GIS Cut Line= 4
      1363905.04      6819037.99      1364640.03      6818924.14
      1364714.63      6818798.81      1365004.99      6817988.04
#Sta/Elev= 30
  4110.4 2379.01  4270.4 2372.29  4282.4 2370.79  4413.9 2367.04  4499.9 2362.14
  4668.8 2356.39  4799.9 2354.24  4854.1 2354.85  4876.2 2353.65  4908.5 2349.02
  4913.2 2348.91  4919.5 2345.98  4928.8 2344.38  4942.8 2344.29  4969.0 2340.24
  4969.4 2339.74  4974.2 2340.24  4993.0 2344.15  4997.6 2346.60  5011.1 2348.31
  5077.9 2348.89  5164.9 2352.47  5234.5 2352.89  5277.0 2355.18  5415.1 2358.62
  5431.1 2360.11  5461.9 2359.51  5690.9 2370.52  5857.2 2381.45  5861.2 2381.61
#Mann=7,-1,0
  4110.4    0.07       0  4499.9   0.035       0  4908.5    0.07       0
  4969.0    0.07       0  4974.2    0.07       0  5690.9    0.16       0
  5857.2    0.07       0
Bank Sta=4969,4974.2
Exp/Cntr=0.3,0.1

Type RM Length L Ch R = 1,14502,494,494,494
BEGIN DESCRIPTION:
Sweetwater Creek Trib 12 26.0
END DESCRIPTION:
XS GIS Cut Line= 3
      1364955.03      6819037.96      1365160.56      6818737.30
      1365254.97      6818638.03
#Sta/Elev= 30
  4635.8 2352.17  4649.3 2352.35  4664.2 2350.57  4679.1 2350.76  4682.3 2350.29
  4694.0 2349.57  4786.8 2348.18  4816.6 2346.60  4837.6 2345.06  4843.6 2344.07
  4879.5 2342.06  4909.4 2342.76  4960.2 2341.90  4966.2 2342.49  4981.1 2338.22
  4996.1 2336.53  4996.8 2335.16  4997.2 2334.66  5001.8 2334.66  5002.2 2335.16
  5009.8 2337.24  5016.7 2345.89  5024.0 2346.89  5038.1 2348.21  5052.3 2348.59
  5059.2 2349.50  5066.4 2348.98  5101.6 2351.81  5108.9 2351.45  5137.0 2353.12
#Mann=4,-1,0
  4635.8   0.035       0  4682.3    0.07       0  4996.8    0.07       0
  5002.2    0.07       0
Bank Sta=4996.8,5002.2
Exp/Cntr=0.3,0.1

Type RM Length L Ch R = 1,14008,498,498,498
BEGIN DESCRIPTION:
Sweetwater Creek Trib 12 25.0
END DESCRIPTION:
XS GIS Cut Line= 3
      1364955.00      6819188.00      1365454.33      6819101.91
      1365705.00      6818938.00
#Sta/Elev= 30
  4493.3 2354.55  4503.4 2354.84  4520.7 2353.53  4525.8 2352.07  4544.0 2351.99
  4594.8 2348.76  4700.3 2345.92  4760.2 2341.41  4797.8 2340.66  4838.3 2339.68
  4874.9 2334.82  4902.8 2334.08  4934.7 2334.35  4939.8 2335.37  4991.9 2331.55
  4992.3 2331.05  4997.4 2331.55  4997.8 2334.14  5003.4 2334.14  5024.7 2340.01
  5053.7 2340.93  5060.5 2342.43  5096.4 2344.75  5147.2 2346.42  5177.4 2350.15
  5191.0 2350.12  5227.8 2350.82  5276.8 2354.28  5286.0 2356.37  5299.5 2356.60
#Mann=6,-1,0
  4493.3    0.07       0  4797.8   0.035       0  4902.8    0.07       0
  4991.9    0.07       0  4997.4    0.07       0  5191.0   0.035       0
Bank Sta=4991.9,4997.4
Exp/Cntr=0.3,0.1

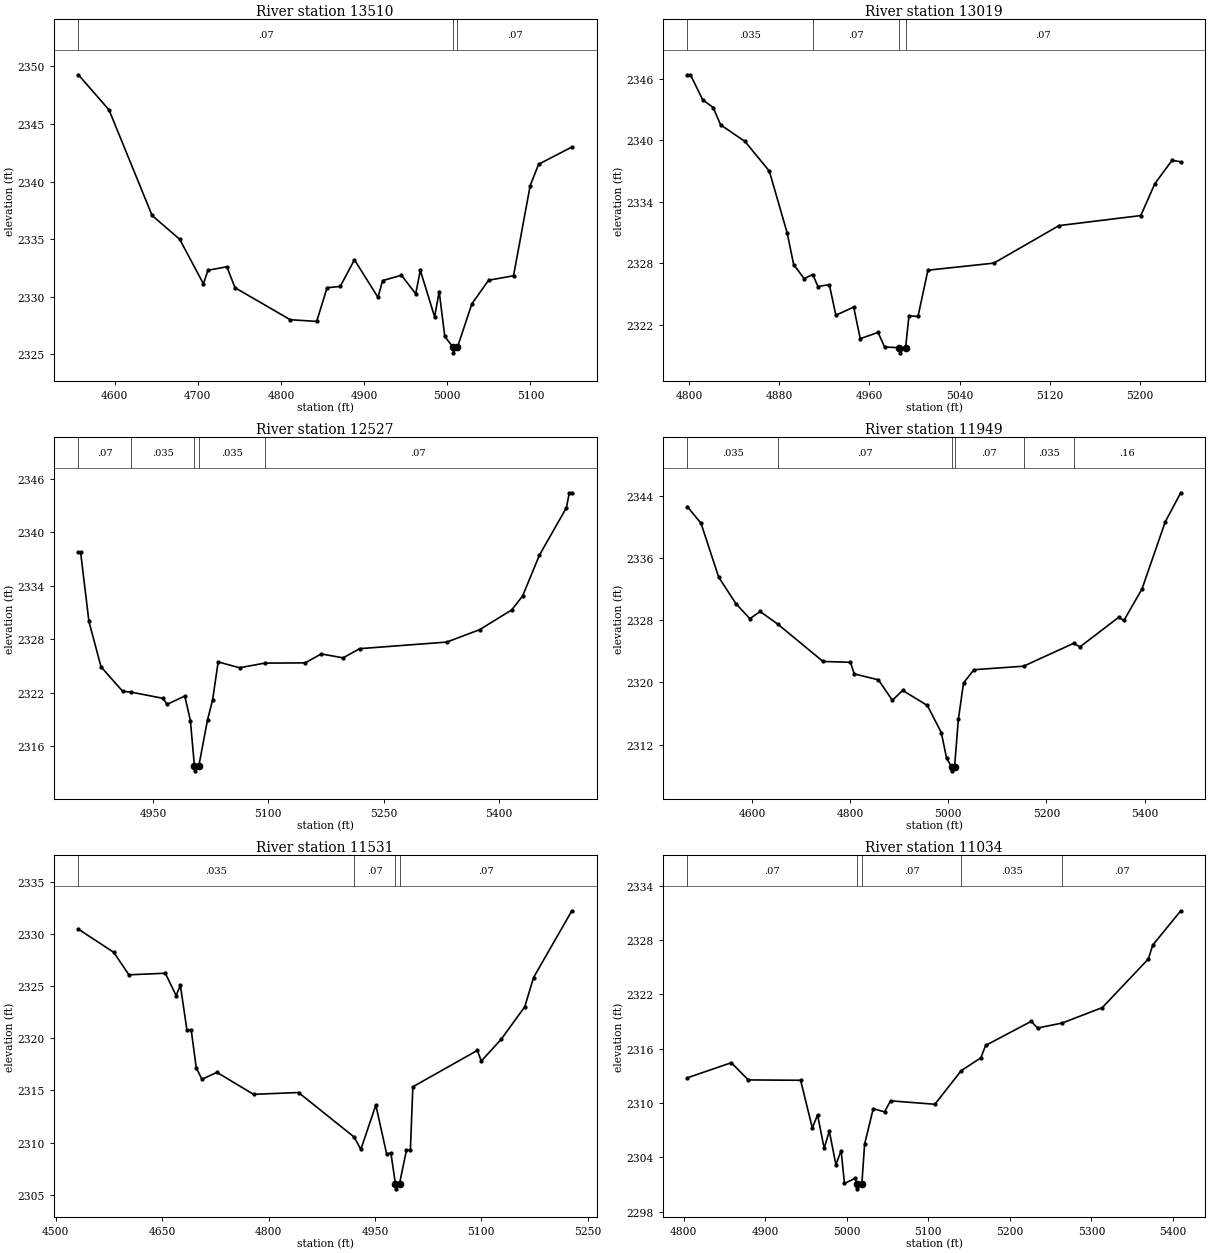
Type RM Length L Ch R = 1,13510,491,491,491
BEGIN DESCRIPTION:
Sweetwater Creek Trib 12 24.0
END DESCRIPTION:
XS GIS Cut Line= 3
      1365005.04      6819737.98      1365405.44      6819547.28
      1365554.96      6819538.00
#Sta/Elev= 30
  4556.5 2349.28  4593.3 2346.23  4645.1 2337.05  4678.3 2334.98  4706.8 2331.11
  4712.3 2332.29  4735.0 2332.59  4744.8 2330.77  4811.2 2327.99  4843.0 2327.84
  4855.5 2330.77  4871.3 2330.88  4888.4 2333.20  4916.7 2329.93  4922.2 2331.39
  4944.9 2331.85  4962.1 2330.24  4967.6 2332.28  4984.8 2328.24  4990.3 2330.44
  4997.0 2326.54  5006.8 2325.61  5007.3 2325.11  5012.3 2325.61  5029.6 2329.37
  5049.7 2331.42  5079.7 2331.81  5099.7 2339.65  5109.8 2341.50  5149.8 2343.00
#Mann=3,-1,0
  4556.5    0.07       0  5006.8    0.07       0  5012.3    0.07       0
Bank Sta=5006.8,5012.3
Exp/Cntr=0.3,0.1

Type RM Length L Ch R = 1,13019,492,492,492
BEGIN DESCRIPTION:
Sweetwater Creek Trib 12 23.0
END DESCRIPTION:
XS GIS Cut Line= 3
      1365205.04      6819987.98      1365379.99      6819888.00
      1365505.02      6819687.96
#Sta/Elev= 30
  4798.5 2346.40  4801.3 2346.40  4812.1 2343.97  4821.5 2343.20  4828.0 2341.52
  4849.6 2339.90  4871.2 2337.01  4887.0 2330.99  4892.8 2327.88  4902.1 2326.52
  4909.7 2326.92  4914.3 2325.75  4924.4 2325.93  4930.2 2322.95  4946.0 2323.74
  4951.8 2320.66  4967.6 2321.27  4973.4 2319.85  4986.4 2319.78  4986.9 2319.28
  4992.0 2319.78  4995.0 2322.89  5003.0 2322.83  5011.8 2327.34  5070.2 2328.03
  5128.0 2331.69  5200.5 2332.67  5212.9 2335.77  5228.2 2338.06  5235.9 2337.91
#Mann=4,-1,0
  4798.5   0.035       0  4909.7    0.07       0  4986.4    0.07       0
  4992.0    0.07       0
Bank Sta=4986.4,4992
Exp/Cntr=0.3,0.1

Type RM Length L Ch R = 1,12527,578,578,578
BEGIN DESCRIPTION:
Sweetwater Creek Trib 12 22.0
END DESCRIPTION:
XS GIS Cut Line= 3
      1365704.98      6820188.04      1365778.73      6820060.30
      1366154.97      6819738.03
#Sta/Elev= 30
  4852.5 2337.75  4855.4 2337.75  4866.2 2330.02  4882.0 2324.92  4910.3 2322.17
  4920.6 2322.10  4962.4 2321.40  4968.2 2320.73  4991.1 2321.65  4998.4 2318.90
  5003.7 2313.77  5004.1 2313.27  5009.3 2313.77  5020.7 2318.98  5027.3 2321.19
  5034.6 2325.48  5062.4 2324.82  5095.2 2325.34  5148.0 2325.37  5168.9 2326.37
  5197.4 2325.93  5218.9 2326.96  5332.4 2327.70  5375.3 2329.09  5417.0 2331.30
  5431.2 2332.86  5453.2 2337.45  5488.3 2342.75  5492.1 2344.43  5495.4 2344.43
#Mann=5,-1,0
  4852.5    0.07       0  4920.6   0.035       0  5003.7   0.035       0
  5009.3   0.035       0  5095.2    0.07       0
Bank Sta=5003.7,5009.3
Exp/Cntr=0.3,0.1

Type RM Length L Ch R = 1,11949,418,418,418
BEGIN DESCRIPTION:
Sweetwater Creek Trib 12 21.0
END DESCRIPTION:
XS GIS Cut Line= 3
      1365755.04      6820637.97      1366155.21      6820287.42
      1366304.99      6819838.02
#Sta/Elev= 30
  4468.0 2342.63  4496.0 2340.47  4532.0 2333.54  4567.1 2330.14  4595.6 2328.20
  4616.5 2329.13  4652.6 2327.49  4744.6 2322.70  4800.6 2322.59  4808.2 2321.10
  4857.5 2320.34  4886.0 2317.70  4906.9 2318.98  4957.2 2317.04  4985.7 2313.56
  4996.5 2310.23  5007.0 2309.13  5007.5 2308.63  5012.7 2309.13  5020.5 2315.28
  5031.0 2319.93  5052.1 2321.64  5153.3 2322.09  5255.6 2325.04  5268.2 2324.57
  5347.2 2328.38  5357.8 2327.97  5394.7 2332.02  5442.1 2340.66  5473.7 2344.40
#Mann=6,-1,0
  4468.0   0.035       0  4652.6    0.07       0  5007.0    0.07       0
  5012.7    0.07       0  5153.3   0.035       0  5255.6    0.16       0
Bank Sta=5007,5012.7
Exp/Cntr=0.3,0.1

Type RM Length L Ch R = 1,11531,497,497,497
BEGIN DESCRIPTION:
Sweetwater Creek Trib 12 20.0
END DESCRIPTION:
XS GIS Cut Line= 3
      1365954.99      6820888.00      1366349.26      6820635.66
      1366554.96      6820538.02
#Sta/Elev= 30
  4531.9 2330.44  4581.8 2328.22  4603.1 2326.07  4654.5 2326.22  4669.7 2324.08
  4675.7 2325.06  4685.0 2320.74  4690.9 2320.82  4698.1 2317.16  4706.1 2316.07
  4727.2 2316.73  4778.8 2314.63  4842.3 2314.80  4920.7 2310.54  4930.2 2309.36
  4951.3 2313.60  4966.6 2308.90  4972.5 2309.02  4978.9 2306.08  4979.4 2305.58
  4984.7 2306.08  4994.5 2309.28  5000.0 2309.28  5003.5 2315.35  5094.4 2318.83
  5100.0 2317.81  5128.2 2319.91  5161.3 2323.01  5173.7 2325.81  5227.7 2332.20
#Mann=4,-1,0
  4531.9   0.035       0  4920.7    0.07       0  4978.9    0.07       0
  4984.7    0.07       0
Bank Sta=4978.9,4984.7
Exp/Cntr=0.3,0.1

Type RM Length L Ch R = 1,11034,482,482,482
BEGIN DESCRIPTION:
Sweetwater Creek Trib 12 19.0
END DESCRIPTION:
XS GIS Cut Line= 3
      1366344.12      6821142.28      1366465.16      6820988.50
      1366602.22      6820602.51
#Sta/Elev= 30
  4804.3 2312.78  4858.3 2314.45  4879.1 2312.55  4943.3 2312.51  4957.7 2307.24
  4964.1 2308.69  4972.2 2304.99  4978.5 2306.90  4986.6 2303.18  4993.0 2304.75
  4997.1 2301.11  5010.1 2301.68  5012.6 2301.02  5013.0 2300.52  5018.4 2301.02
  5021.8 2305.46  5032.4 2309.37  5046.3 2309.02  5053.6 2310.24  5108.0 2309.86
  5140.3 2313.57  5164.4 2314.99  5170.3 2316.36  5226.2 2319.02  5234.0 2318.28
  5264.4 2318.84  5313.4 2320.54  5369.9 2325.91  5375.2 2327.43  5409.6 2331.23
#Mann=5,-1,0
  4804.3    0.07       0  5012.6    0.07       0  5018.4    0.07       0
  5140.3   0.035       0  5264.4    0.07       0
Bank Sta=5012.6,5018.4
Exp/Cntr=0.3,0.1

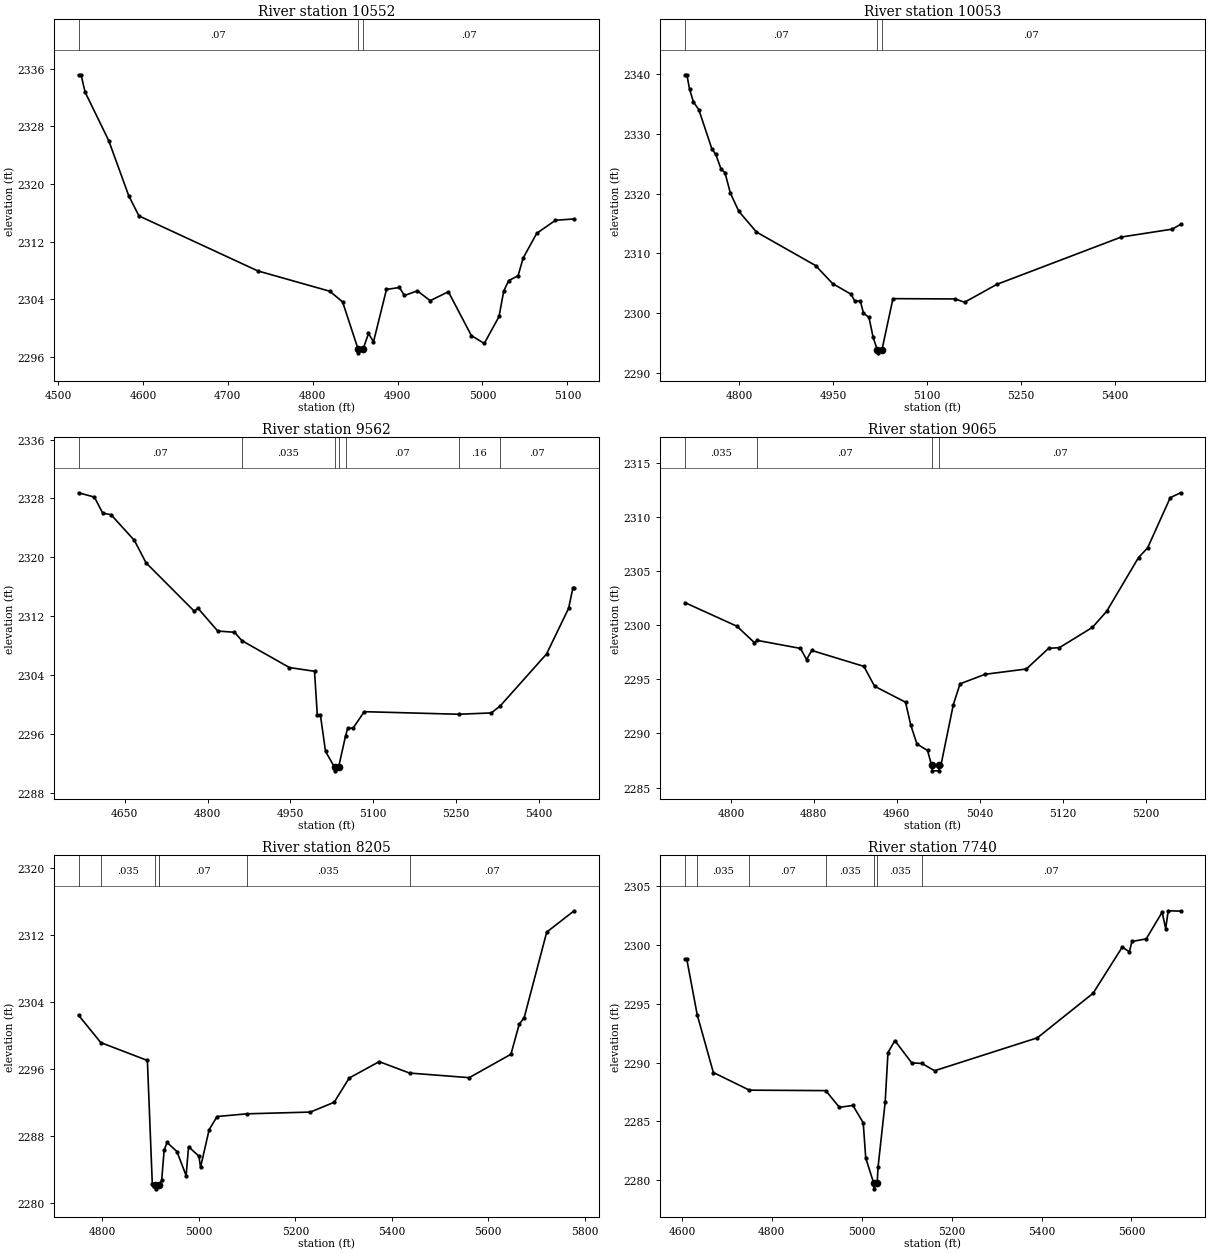
Type RM Length L Ch R = 1,10552,499,499,499
BEGIN DESCRIPTION:
Sweetwater Creek Trib 12 18.0
END DESCRIPTION:
XS GIS Cut Line= 3
      1366604.98      6821488.04      1366859.62      6821085.99
      1366905.00      6820987.99
#Sta/Elev= 30
  4524.1 2335.18  4527.1 2335.18  4531.8 2332.79  4559.7 2326.03  4583.3 2318.36
  4595.3 2315.57  4735.2 2307.93  4820.1 2305.10  4835.2 2303.62  4853.5 2297.04
  4853.9 2296.54  4859.3 2297.04  4865.7 2299.23  4871.6 2298.07  4886.9 2305.35
  4902.1 2305.62  4908.1 2304.51  4923.3 2305.15  4938.4 2303.79  4959.8 2305.03
  4986.9 2298.94  5002.1 2297.84  5019.5 2301.59  5025.0 2305.11  5030.8 2306.58
  5041.9 2307.24  5047.9 2309.71  5063.9 2313.15  5086.0 2314.96  5108.0 2315.15
#Mann=3,-1,0
  4524.1    0.07       0  4853.5    0.07       0  4859.3    0.07       0
Bank Sta=4853.5,4859.3
Exp/Cntr=0.3,0.1

Type RM Length L Ch R = 1,10053,491,491,491
BEGIN DESCRIPTION:
Sweetwater Creek Trib 12 17.0
END DESCRIPTION:
XS GIS Cut Line= 3
      1366755.02      6821637.98      1366988.23      6821471.57
      1367132.75      6820986.96
#Sta/Elev= 30
  4713.5 2339.91  4716.5 2339.91  4720.8 2337.52  4727.0 2335.35  4735.6 2334.07
  4756.5 2327.49  4762.6 2326.60  4771.2 2324.10  4777.4 2323.52  4786.0 2320.09
  4799.5 2317.04  4827.8 2313.56  4922.3 2307.94  4949.5 2304.92  4979.0 2303.14
  4985.1 2301.96  4993.7 2302.01  4998.8 2299.97  5007.6 2299.26  5014.2 2295.92
  5020.9 2293.82  5021.4 2293.32  5028.3 2293.82  5045.9 2302.40  5145.4 2302.35
  5160.3 2301.79  5211.7 2304.78  5410.7 2312.72  5492.5 2314.05  5505.7 2314.86
#Mann=3,-1,0
  4713.5    0.07       0  5020.9    0.07       0  5028.3    0.07       0
Bank Sta=5020.9,5028.3
Exp/Cntr=0.3,0.1

Type RM Length L Ch R = 1,9562,497,497,497
BEGIN DESCRIPTION:
Sweetwater Creek Trib 12 16.0
END DESCRIPTION:
XS GIS Cut Line= 3
      1367004.96      6821938.02      1367368.46      6821701.63
      1367355.00      6821238.03
#Sta/Elev= 30
  4566.4 2328.77  4595.1 2328.19  4610.2 2326.01  4625.4 2325.79  4667.6 2322.30
  4688.7 2319.26  4776.3 2312.67  4782.3 2313.13  4818.5 2310.00  4848.8 2309.84
  4862.2 2308.70  4948.3 2305.05  4993.7 2304.54  4998.7 2298.64  5004.3 2298.64
  5013.6 2293.67  5029.9 2291.53  5030.4 2291.03  5037.3 2291.53  5049.8 2295.74
  5053.7 2296.79  5063.7 2296.85  5083.7 2299.06  5254.5 2298.71  5313.8 2298.89
  5329.9 2299.84  5413.8 2306.89  5453.8 2313.10  5461.3 2315.79  5463.8 2315.79
#Mann=7,-1,0
  4566.4    0.07       0  4862.2   0.035       0  5029.9   0.035       0
  5037.3   0.035       0  5049.8    0.07       0  5254.5    0.16       0
  5329.9    0.07       0
Bank Sta=5029.9,5037.3
Exp/Cntr=0.3,0.1

Type RM Length L Ch R = 1,9065,860,860,860
BEGIN DESCRIPTION:
Sweetwater Creek Trib 12 15.0
END DESCRIPTION:
XS GIS Cut Line= 3
      1367683.81      6821697.07      1367634.51      6821457.79
      1367555.01      6821238.03
#Sta/Elev= 30
  4755.7 2302.09  4805.8 2299.91  4822.6 2298.40  4825.5 2298.60  4867.1 2297.86
  4872.9 2296.83  4878.0 2297.67  4928.3 2296.20  4938.5 2294.37  4968.4 2292.89
  4973.5 2290.76  4979.4 2289.03  4989.6 2288.43  4993.6 2287.05  4994.1 2286.55
  5000.5 2286.55  5001.0 2287.05  5002.5 2287.05  5014.5 2292.67  5021.0 2294.59
  5045.1 2295.47  5084.9 2295.96  5106.4 2297.87  5116.8 2297.93  5148.7 2299.81
  5162.4 2301.29  5193.1 2306.26  5201.8 2307.14  5223.7 2311.79  5233.7 2312.24
#Mann=4,-1,0
  4755.7   0.035       0  4825.5    0.07       0  4993.6    0.07       0
  5001.0    0.07       0
Bank Sta=4993.6,5001
Exp/Cntr=0.3,0.1

Type RM Length L Ch R = 1,8205,465,465,465
BEGIN DESCRIPTION:
Sweetwater Creek Trib 12 14.0
END DESCRIPTION:
XS GIS Cut Line= 3
      1368354.99      6821637.97      1368305.49      6821393.23
      1367555.04      6821188.01
#Sta/Elev= 30
  4750.3 2302.44  4796.5 2299.17  4893.1 2297.04  4903.3 2282.32  4909.7 2282.24
  4910.2 2281.74  4917.3 2282.24  4917.7 2282.28  4922.7 2282.74  4927.8 2286.34
  4933.9 2287.27  4954.3 2286.19  4973.4 2283.32  4978.5 2286.76  5000.0 2285.63
  5003.3 2284.31  5021.2 2288.80  5037.8 2290.36  5099.2 2290.68  5231.1 2290.89
  5280.4 2292.06  5311.5 2294.94  5373.7 2296.90  5436.6 2295.54  5560.3 2294.99
  5646.9 2297.78  5664.0 2301.35  5674.4 2302.15  5721.1 2312.34  5778.0 2314.88
#Mann=7,-1,0
  4750.3    0.07       0  4796.5   0.035       0  4909.7    0.07       0
  4917.3   0.035       0  4917.7    0.07       0  5099.2   0.035       0
  5436.6    0.07       0
Bank Sta=4909.7,4917.3
Exp/Cntr=0.3,0.1

Type RM Length L Ch R = 1,7740,655,655,655
BEGIN DESCRIPTION:
Sweetwater Creek Trib 12 4156
END DESCRIPTION:
XS GIS Cut Line= 3
      1368438.30      6821371.00      1368415.84      6820978.55
      1367799.27      6820627.50
#Sta/Elev= 30
  4606.9 2298.79  4610.9 2298.79  4634.1 2294.06  4670.0 2289.15  4750.2 2287.65
  4919.9 2287.61  4950.5 2286.19  4980.5 2286.35  5003.4 2284.88  5009.0 2281.88
  5026.6 2279.76  5027.1 2279.26  5034.6 2279.76  5036.3 2281.08  5052.2 2286.62
  5058.5 2290.85  5073.8 2291.86  5111.3 2289.97  5134.1 2289.92  5162.1 2289.30
  5390.8 2292.10  5514.8 2295.89  5579.6 2299.81  5595.5 2299.41  5601.2 2300.29
  5632.9 2300.51  5668.4 2302.78  5676.2 2301.39  5681.9 2302.90  5709.5 2302.87
#Mann=7,-1,0
  4606.9    0.07       0  4634.1   0.035       0  4750.2    0.07       0
  4919.9   0.035       0  5026.6   0.035       0  5034.6   0.035       0
  5134.1    0.07       0
Bank Sta=5026.6,5034.6
Exp/Cntr=0.3,0.1

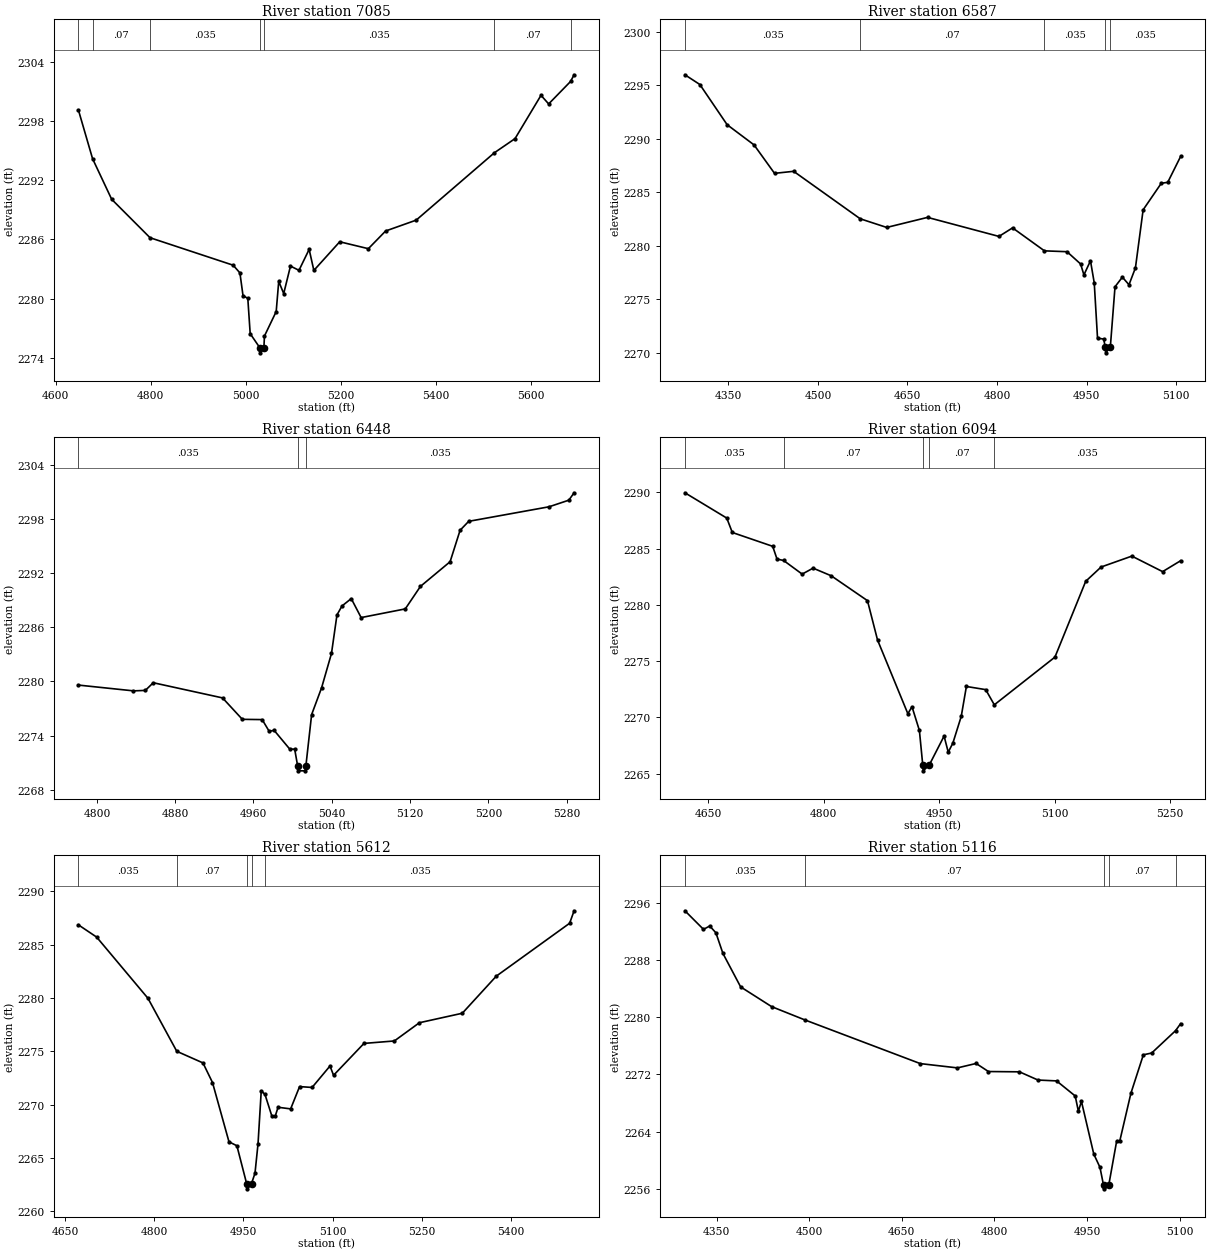
Type RM Length L Ch R = 1,7085,498,498,498
BEGIN DESCRIPTION:
Sweetwater Creek Trib 12 13.0
END DESCRIPTION:
XS GIS Cut Line= 3
      1368482.97      6821404.02      1368706.96      6821132.35
      1368954.98      6820488.04
#Sta/Elev= 30
  4647.9 2299.10  4677.7 2294.17  4717.9 2290.06  4798.6 2286.17  4973.3 2283.39
  4987.6 2282.61  4994.1 2280.31  5004.2 2280.03  5009.2 2276.46  5029.7 2275.02
  5030.2 2274.52  5038.0 2275.02  5039.2 2276.22  5063.9 2278.70  5069.2 2281.75
  5079.7 2280.52  5093.9 2283.30  5111.8 2282.87  5133.2 2284.99  5143.1 2282.86
  5197.5 2285.76  5257.7 2285.06  5294.0 2286.85  5358.3 2287.95  5522.8 2294.77
  5566.2 2296.20  5620.8 2300.58  5636.9 2299.71  5682.9 2301.98  5690.4 2302.66
#Mann=7,-1,0
  4647.9   0.035       0  4677.7    0.07       0  4798.6   0.035       0
  5029.7   0.035       0  5038.0   0.035       0  5522.8    0.07       0
  5682.9   0.035       0
Bank Sta=5029.7,5038
Exp/Cntr=0.3,0.1

Type RM Length L Ch R = 1,6587,139,139,139
BEGIN DESCRIPTION:
Sweetwater Creek Trib 12 12.0
END DESCRIPTION:
XS GIS Cut Line= 3
      1368510.24      6821445.03      1369164.35      6821137.48
      1369205.01      6821037.97
#Sta/Elev= 30
  4277.2 2295.98  4302.2 2295.07  4347.9 2291.31  4393.0 2289.42  4427.3 2286.76
  4459.3 2286.95  4570.8 2282.51  4615.2 2281.70  4683.6 2282.64  4803.2 2280.86
  4826.0 2281.66  4879.4 2279.51  4917.2 2279.43  4940.0 2278.28  4945.5 2277.26
  4956.5 2278.58  4962.8 2276.52  4968.3 2271.34  4978.6 2271.26  4981.4 2270.47
  4981.9 2269.97  4989.7 2270.47  4997.6 2276.15  5009.9 2277.05  5021.0 2276.34
  5031.8 2277.92  5044.7 2283.35  5075.1 2285.83  5085.9 2285.92  5107.5 2288.34
#Mann=5,-1,0
  4277.2   0.035       0  4570.8    0.07       0  4879.4   0.035       0
  4981.4   0.035       0  4989.7   0.035       0
Bank Sta=4981.4,4989.7
Exp/Cntr=0.3,0.1

Type RM Length L Ch R = 1,6448,354,354,354
BEGIN DESCRIPTION:
Sweetwater Creek Trib 12 4155
END DESCRIPTION:
XS GIS Cut Line= 3
      1369039.40      6821252.91      1369255.76      6821219.68
      1369540.31      6821177.90
#Sta/Elev= 30
  4781.1 2279.60  4837.4 2278.96  4849.5 2279.01  4857.6 2279.86  4928.4 2278.18
  4948.6 2275.81  4968.9 2275.78  4976.0 2274.49  4981.1 2274.59  4997.1 2272.51
  5002.1 2272.51  5005.2 2270.61  5005.7 2270.11  5013.0 2270.11  5013.5 2270.61
  5019.4 2276.33  5029.6 2279.30  5039.7 2283.10  5045.3 2287.36  5050.4 2288.35
  5059.9 2289.17  5070.0 2287.07  5115.1 2288.03  5130.6 2290.52  5160.9 2293.25
  5171.1 2296.73  5179.9 2297.72  5262.0 2299.33  5282.2 2300.06  5287.6 2300.88
#Mann=3,-1,0
  4781.1   0.035       0  5005.2   0.035       0  5013.5   0.035       0
Bank Sta=5005.2,5013.5
Exp/Cntr=0.3,0.1

Type RM Length L Ch R = 1,6094,482,482,482
BEGIN DESCRIPTION:
Sweetwater Creek Trib 12 11.0
END DESCRIPTION:
XS GIS Cut Line= 3
      1368655.01      6821538.00      1369004.65      6821387.65
      1369268.37      6821394.14
#Sta/Elev= 30
  4619.4 2289.97  4673.8 2287.72  4681.0 2286.44  4733.5 2285.21  4739.1 2284.08
  4747.7 2283.95  4771.8 2282.74  4786.0 2283.27  4809.6 2282.59  4856.7 2280.38
  4869.8 2276.88  4909.2 2270.33  4914.6 2270.95  4924.2 2268.84  4928.6 2265.75
  4929.1 2265.25  4936.9 2265.75  4956.3 2268.34  4961.7 2266.91  4967.7 2267.71
  4978.6 2270.09  4985.3 2272.75  5010.4 2272.47  5021.6 2271.12  5100.4 2275.36
  5140.4 2282.10  5160.4 2283.37  5200.4 2284.34  5240.4 2282.96  5263.8 2283.93
#Mann=5,-1,0
  4619.4   0.035       0  4747.7    0.07       0  4928.6    0.07       0
  4936.9    0.07       0  5021.6   0.035       0
Bank Sta=4928.6,4936.9
Exp/Cntr=0.3,0.1

Type RM Length L Ch R = 1,5612,496,496,496
BEGIN DESCRIPTION:
Sweetwater Creek Trib 12 10.0
END DESCRIPTION:
XS GIS Cut Line= 3
      1368754.99      6821738.00      1369074.59      6821808.58
      1369355.01      6821387.99
#Sta/Elev= 30
  4672.7 2286.87  4703.4 2285.72  4789.6 2279.98  4838.0 2275.01  4882.0 2273.92
  4898.0 2272.08  4925.7 2266.52  4939.0 2266.15  4955.3 2262.61  4955.8 2262.11
  4963.6 2262.61  4969.4 2263.58  4974.5 2266.34  4979.9 2271.31  4986.2 2270.96
  4997.7 2268.94  5003.4 2268.94  5008.2 2269.76  5029.3 2269.61  5044.3 2271.70
  5065.3 2271.62  5095.4 2273.63  5101.4 2272.76  5152.5 2275.75  5203.5 2275.98
  5245.6 2277.69  5317.7 2278.58  5374.8 2282.06  5498.0 2287.02  5505.5 2288.19
#Mann=5,-1,0
  4672.7   0.035       0  4838.0    0.07       0  4955.3   0.035       0
  4963.6    0.07       0  4986.2   0.035       0
Bank Sta=4955.3,4963.6
Exp/Cntr=0.3,0.1

Type RM Length L Ch R = 1,5116,496,496,496
BEGIN DESCRIPTION:
Sweetwater Creek Trib 12 9.0
END DESCRIPTION:
XS GIS Cut Line= 3
      1368655.00      6822138.00      1369353.78      6822077.49
      1369455.04      6822088.00
#Sta/Elev= 30
  4298.6 2294.89  4328.7 2292.29  4338.8 2292.76  4348.8 2291.81  4360.2 2288.92
  4388.9 2284.24  4439.1 2281.48  4492.7 2279.63  4680.0 2273.51  4740.2 2272.91
  4770.4 2273.53  4790.4 2272.40  4840.6 2272.36  4870.7 2271.21  4900.8 2271.09
  4931.0 2268.98  4936.1 2266.85  4941.1 2268.22  4961.1 2260.85  4971.1 2259.00
  4976.9 2256.49  4977.4 2255.99  4985.3 2256.49  4998.1 2262.65  5003.1 2262.65
  5021.3 2269.38  5041.4 2274.74  5054.9 2274.99  5093.5 2278.11  5101.8 2279.10
#Mann=5,-1,0
  4298.6   0.035       0  4492.7    0.07       0  4976.9    0.07       0
  4985.3    0.07       0  5093.5   0.035       0
Bank Sta=4976.9,4985.3
Exp/Cntr=0.3,0.1

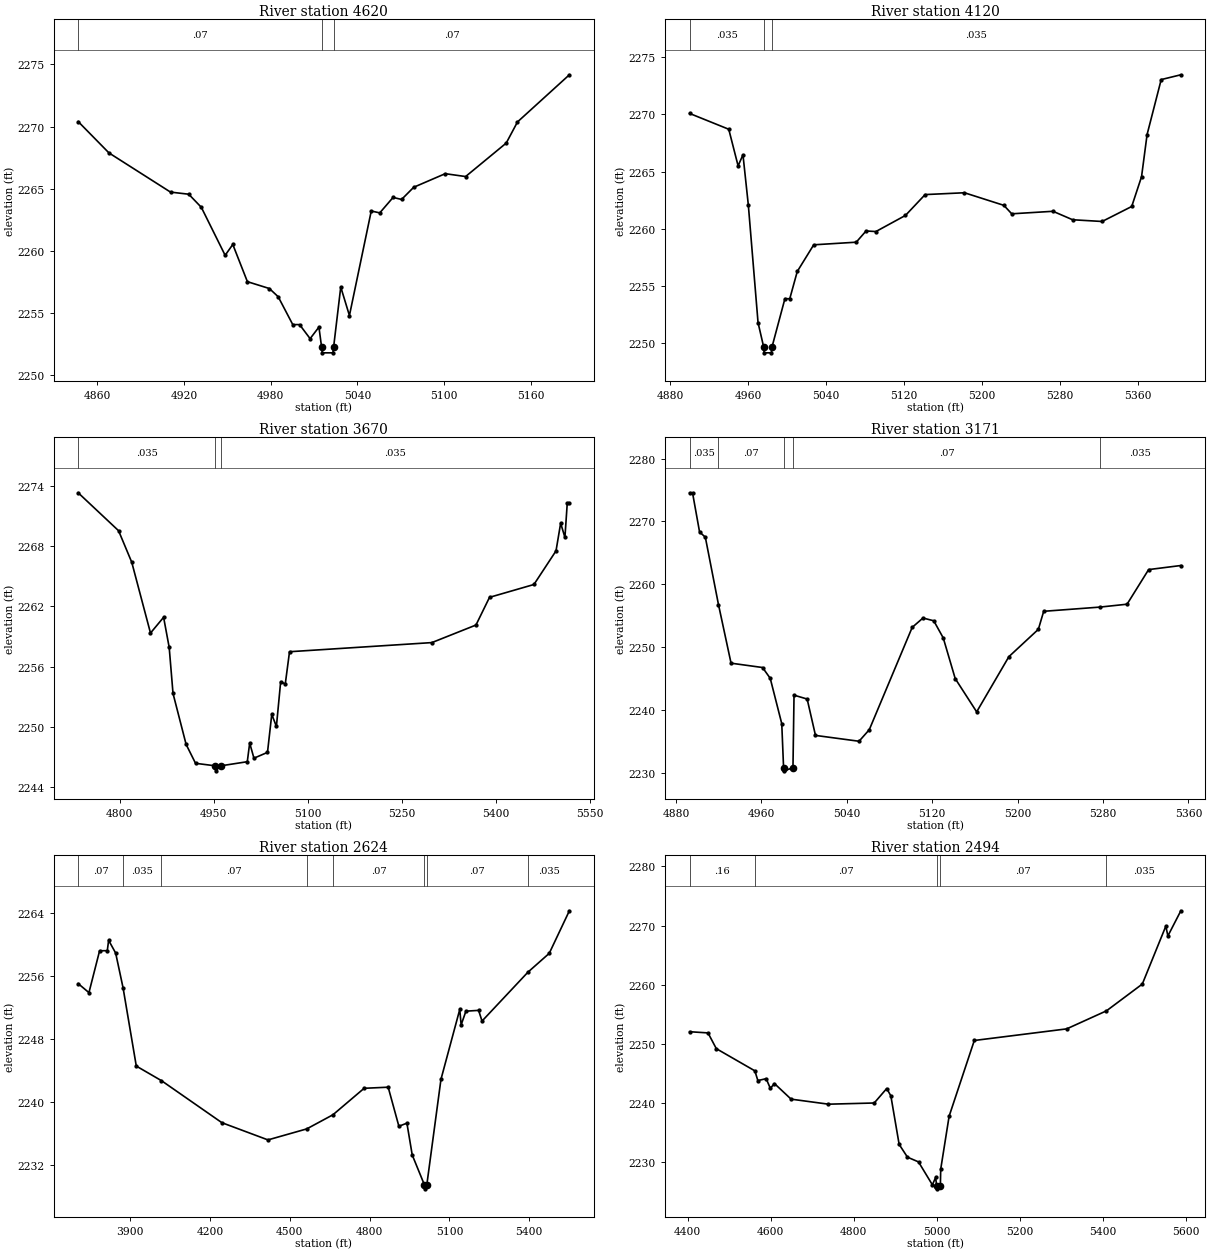
Type RM Length L Ch R = 1,4620,500,500,500
BEGIN DESCRIPTION:
Sweetwater Creek Trib 12 8.0
END DESCRIPTION:
XS GIS Cut Line= 3
      1369104.97      6822487.99      1369248.92      6822540.42
      1369405.01      6822437.99
#Sta/Elev= 30
  4846.8 2270.40  4868.1 2267.88  4910.7 2264.73  4923.3 2264.56  4932.0 2263.51
  4948.5 2259.65  4953.8 2260.52  4963.9 2257.53  4979.1 2256.98  4985.2 2256.32
  4995.3 2254.08  5000.0 2254.08  5007.3 2252.95  5013.4 2253.88  5015.2 2252.31
  5015.7 2251.81  5023.1 2251.81  5023.6 2252.31  5028.5 2257.10  5034.5 2254.81
  5049.6 2263.21  5055.5 2263.06  5064.7 2264.30  5070.6 2264.14  5079.0 2265.12
  5100.8 2266.21  5114.9 2265.98  5143.0 2268.67  5150.8 2270.37  5186.7 2274.16
#Mann=3,-1,0
  4846.8    0.07       0  5015.2    0.07       0  5023.6    0.07       0
Bank Sta=5015.2,5023.6
Exp/Cntr=0.3,0.1

Type RM Length L Ch R = 1,4120,450,450,450
BEGIN DESCRIPTION:
Sweetwater Creek Trib 12 7.0
END DESCRIPTION:
XS GIS Cut Line= 3
      1369204.97      6822988.00      1369304.85      6822997.24
      1369704.99      6822938.00
#Sta/Elev= 30
  4899.7 2270.09  4939.9 2268.71  4949.5 2265.51  4954.5 2266.48  4960.0 2262.10
  4970.0 2251.81  4975.8 2249.67  4976.3 2249.17  4983.8 2249.17  4984.3 2249.67
  4997.6 2253.90  5002.6 2253.90  5010.3 2256.28  5027.2 2258.61  5070.9 2258.84
  5081.0 2259.82  5091.1 2259.77  5121.5 2261.18  5141.7 2263.00  5182.1 2263.16
  5222.6 2262.06  5230.7 2261.32  5273.1 2261.54  5293.3 2260.80  5323.6 2260.65
  5354.0 2261.96  5364.1 2264.56  5369.8 2268.25  5384.3 2273.05  5404.5 2273.47
#Mann=3,-1,0
  4899.7   0.035       0  4975.8   0.035       0  4984.3   0.035       0
Bank Sta=4975.8,4984.3
Exp/Cntr=0.3,0.1

Type RM Length L Ch R = 1,3670,499,499,499
BEGIN DESCRIPTION:
Sweetwater Creek Trib 12 6.0
END DESCRIPTION:
XS GIS Cut Line= 3
      1369304.97      6823588.04      1369454.82      6823368.02
      1369805.03      6822987.97
#Sta/Elev= 30
  4733.8 2273.32  4798.2 2269.54  4819.2 2266.40  4849.1 2259.34  4870.0 2260.91
  4878.9 2257.91  4885.0 2253.32  4905.9 2248.24  4920.9 2246.36  4952.4 2246.11
  4952.9 2245.61  4961.2 2246.11  5003.4 2246.52  5007.2 2248.38  5014.0 2246.87
  5035.6 2247.45  5042.4 2251.24  5049.8 2250.03  5056.6 2254.50  5063.9 2254.25
  5070.7 2257.48  5297.6 2258.39  5367.9 2260.14  5389.5 2262.90  5460.3 2264.18
  5495.5 2267.53  5502.9 2270.29  5509.7 2268.87  5513.4 2272.27  5516.8 2272.27
#Mann=3,-1,0
  4733.8   0.035       0  4952.4   0.035       0  4961.2   0.035       0
Bank Sta=4952.4,4961.2
Exp/Cntr=0.3,0.1

Type RM Length L Ch R = 1,3171,547,547,547
BEGIN DESCRIPTION:
Sweetwater Creek Trib 12 5.0
END DESCRIPTION:
XS GIS Cut Line= 3
      1369804.99      6823637.98      1369764.64      6823538.55
      1369805.00      6823187.97
#Sta/Elev= 30
  4892.7 2274.57  4895.4 2274.57  4902.0 2268.33  4907.4 2267.50  4919.7 2256.78
  4931.5 2247.44  4961.0 2246.75  4968.2 2245.03  4979.0 2237.81  4980.7 2230.80
  4981.2 2230.30  4989.5 2230.80  4990.5 2242.35  5002.8 2241.73  5010.6 2235.94
  5051.4 2235.01  5061.0 2236.85  5101.2 2253.14  5111.3 2254.63  5121.4 2254.19
  5130.3 2251.46  5141.5 2244.99  5161.6 2239.69  5191.8 2248.48  5219.4 2252.83
  5224.4 2255.70  5277.1 2256.37  5302.5 2256.83  5322.7 2262.34  5352.9 2262.99
#Mann=5,-1,0
  4892.7   0.035       0  4919.7    0.07       0  4980.7    0.07       0
  4989.5    0.07       0  5277.1   0.035       0
Bank Sta=4980.7,4989.5
Exp/Cntr=0.3,0.1

Type RM Length L Ch R = 1,2624,130,130,130
BEGIN DESCRIPTION:
Sweetwater Creek Trib 12 4.0
END DESCRIPTION:
XS GIS Cut Line= 3
      1370300.55      6824928.28      1370179.91      6823638.21
      1370102.11      6823093.04
#Sta/Elev= 30
  3704.3 2255.04  3744.8 2253.89  3784.9 2259.22  3813.8 2259.23  3818.8 2260.55
  3845.2 2258.93  3873.1 2254.50  3922.8 2244.54  4017.5 2242.68  4244.6 2237.33
  4417.7 2235.14  4563.4 2236.54  4662.0 2238.34  4779.2 2241.71  4869.6 2241.85
  4909.8 2236.88  4940.0 2237.27  4960.0 2233.22  5005.9 2229.41  5006.4 2228.91
  5014.8 2229.41  5068.0 2242.85  5138.7 2251.75  5143.8 2249.78  5161.8 2251.53
  5209.5 2251.63  5222.4 2250.27  5395.1 2256.50  5475.0 2258.89  5550.7 2264.31
#Mann=8,-1,0
  3704.3    0.07       0  3873.1   0.035       0  4017.5    0.07       0
  4563.4    0.16       0  4662.0    0.07       0  5005.9    0.07       0
  5014.8    0.07       0  5395.1   0.035       0
Bank Sta=5005.9,5014.8
Exp/Cntr=0.3,0.1

Type RM Length L Ch R = 1,2494,788,788,788
BEGIN DESCRIPTION:
Sweetwater Creek Trib 12 3.0
END DESCRIPTION:
XS GIS Cut Line= 3
      1370302.40      6824232.21      1370310.58      6823637.37
      1370224.87      6823056.15
#Sta/Elev= 30
  4405.1 2252.06  4449.3 2251.86  4469.3 2249.20  4562.1 2245.45  4569.3 2243.81
  4589.3 2244.13  4599.3 2242.50  4609.3 2243.30  4649.3 2240.67  4739.3 2239.82
  4849.4 2240.02  4879.4 2242.46  4889.4 2241.24  4909.4 2233.03  4929.4 2230.87
  4956.0 2230.07  4989.4 2226.20  4997.2 2227.44  4999.7 2226.02  5000.2 2225.52
  5008.6 2226.02  5009.5 2228.86  5029.7 2237.79  5090.3 2250.58  5312.7 2252.54
  5408.5 2255.59  5494.7 2260.11  5551.3 2269.89  5556.3 2268.24  5587.5 2272.49
#Mann=5,-1,0
  4405.1    0.16       0  4562.1    0.07       0  4999.7    0.07       0
  5008.6    0.07       0  5408.5   0.035       0
Bank Sta=4999.7,5008.6
Exp/Cntr=0.3,0.1