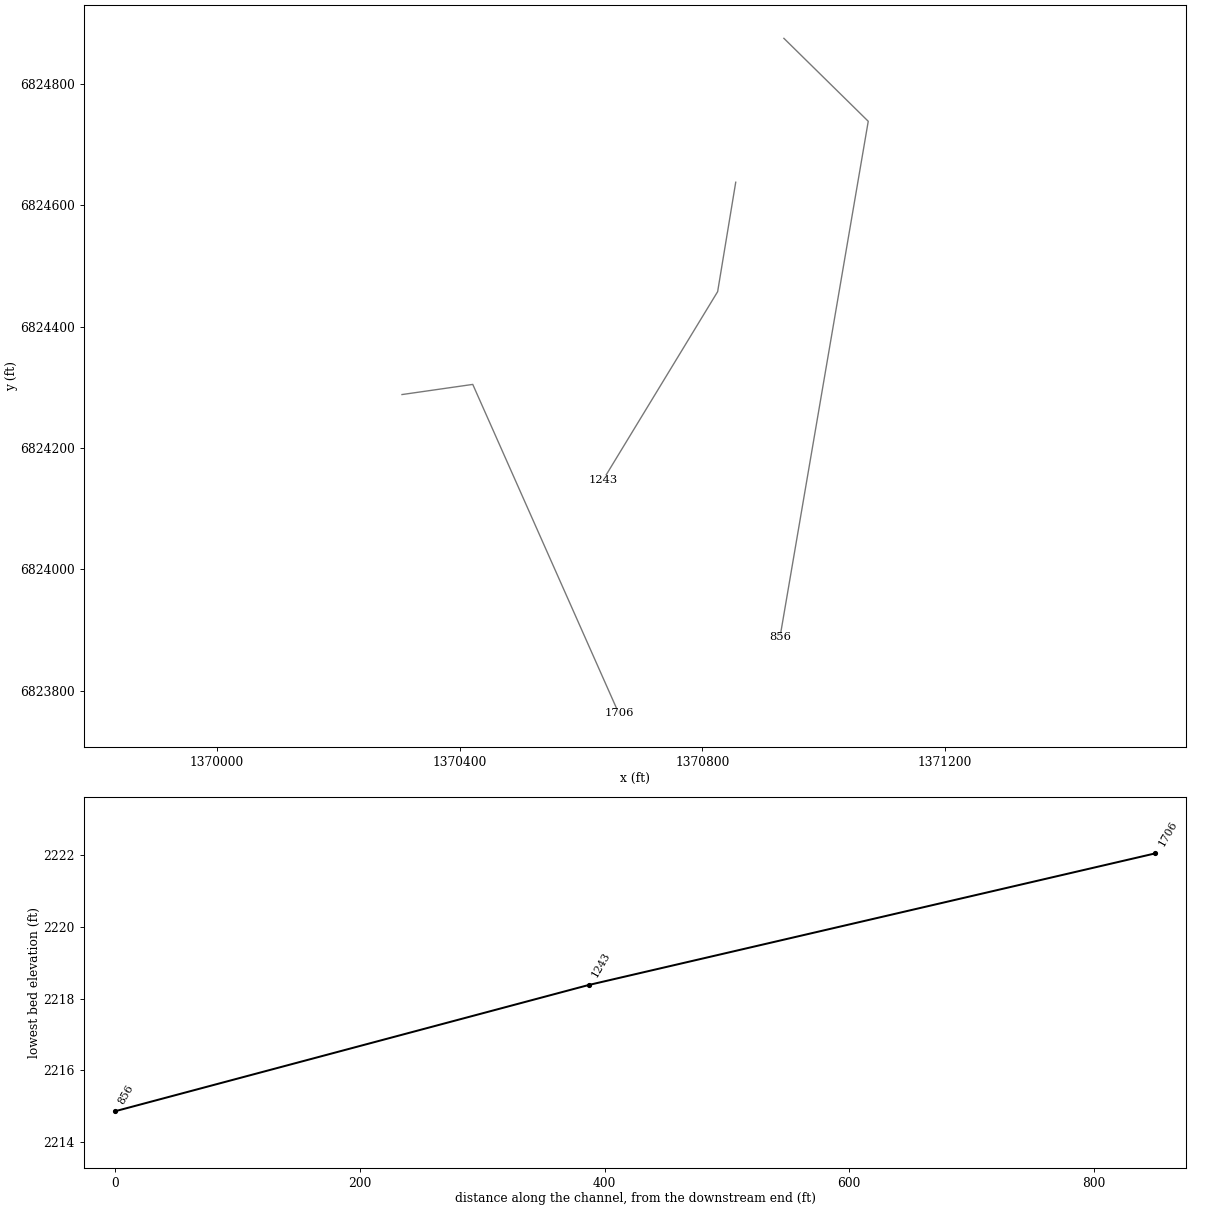
HEC-RAS study Sweetwater Creek Trib 12.prj: Sweetwater Creek Trib 12 Base Level Engineering

--- Sweetwater Creek Trib 12.g01 (geometry) --- (continued)

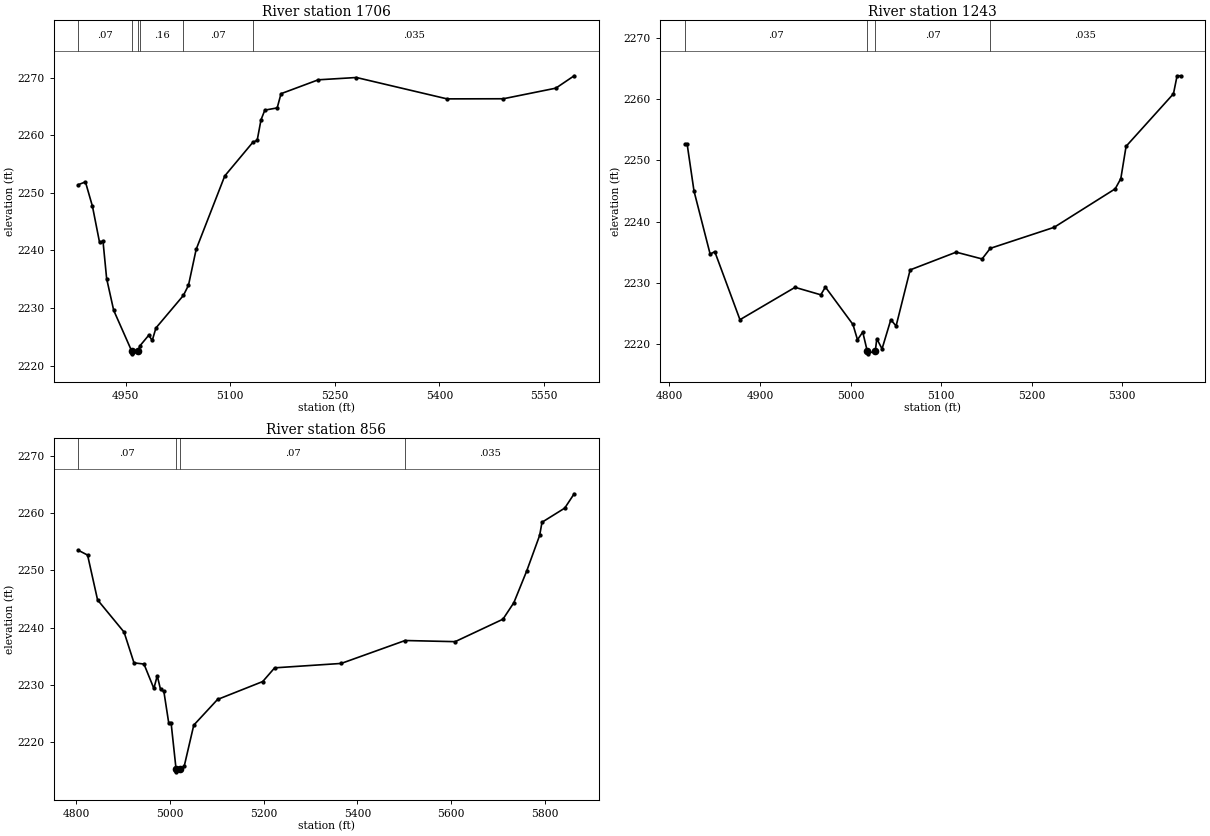
Type RM Length L Ch R = 1,1706,463,463,463
BEGIN DESCRIPTION:
Sweetwater Creek Trib 12 2.0
END DESCRIPTION:
XS GIS Cut Line= 3
      1370304.96      6824287.99      1370421.57      6824304.71
      1370662.25      6823762.53
#Sta/Elev= 30
  4882.2 2251.42  4892.3 2251.90  4902.4 2247.64  4912.5 2241.43  4917.5 2241.60
  4922.7 2235.12  4932.8 2229.61  4958.6 2222.55  4959.1 2222.05  4967.6 2222.55
  4970.6 2223.46  4983.1 2225.28  4988.1 2224.37  4993.4 2226.54  5032.8 2232.19
  5040.1 2233.96  5051.1 2240.19  5092.1 2252.93  5132.5 2258.79  5138.6 2259.11
  5144.1 2262.68  5149.6 2264.36  5167.3 2264.74  5172.8 2267.21  5226.2 2269.62
  5280.9 2270.02  5410.9 2266.31  5491.6 2266.33  5566.9 2268.17  5593.2 2270.32
#Mann=6,-1,0
  4882.2    0.07       0  4958.6    0.07       0  4967.6    0.07       0
  4970.6    0.16       0  5032.8    0.07       0  5132.5   0.035       0
Bank Sta=4958.6,4967.6
Exp/Cntr=0.3,0.1

Type RM Length L Ch R = 1,1243,387,387,387
BEGIN DESCRIPTION:
Sweetwater Creek Trib 12 1.0
END DESCRIPTION:
XS GIS Cut Line= 3
      1370854.99      6824637.95      1370825.17      6824457.60
      1370635.85      6824146.36
#Sta/Elev= 30
  4817.2 2252.68  4819.7 2252.68  4827.3 2244.98  4845.1 2234.68  4850.2 2235.09
  4878.0 2223.96  4938.8 2229.25  4967.2 2228.03  4972.3 2229.29  5002.7 2223.18
  5007.7 2220.68  5013.5 2221.94  5018.4 2218.88  5018.9 2218.38  5027.4 2218.88
  5029.0 2220.85  5034.8 2219.19  5044.5 2223.96  5050.3 2222.93  5065.8 2232.10
  5116.6 2235.00  5145.2 2233.89  5154.2 2235.62  5224.7 2239.06  5292.1 2245.35
  5298.3 2247.02  5304.1 2252.30  5356.4 2260.89  5360.4 2263.83  5364.3 2263.83
#Mann=4,-1,0
  4817.2    0.07       0  5018.4    0.07       0  5027.4    0.07       0
  5154.2   0.035       0
Bank Sta=5018.4,5027.4
Exp/Cntr=0.3,0.1

Type RM Length L Ch R = 1,856,0,0,0
BEGIN DESCRIPTION:
Sweetwater Creek Trib 12 0.1
END DESCRIPTION:
XS GIS Cut Line= 3
      1370934.36      6824875.09      1371073.40      6824738.37
      1370927.96      6823888.23
#Sta/Elev= 30
  4805.0 2253.52  4824.6 2252.69  4845.9 2244.87  4902.4 2239.25  4923.6 2233.88
  4944.9 2233.67  4966.0 2229.41  4973.2 2231.63  4980.2 2229.24  4987.3 2228.90
  4997.6 2223.44  5002.7 2223.44  5013.3 2215.36  5013.8 2214.86  5022.4 2215.36
  5030.8 2215.87  5051.1 2223.01  5101.8 2227.49  5198.2 2230.62  5223.6 2233.01
  5365.6 2233.78  5501.9 2237.78  5608.6 2237.58  5710.6 2241.50  5733.9 2244.39
  5761.3 2249.92  5788.9 2256.13  5793.9 2258.42  5842.4 2260.89  5862.5 2263.39
#Mann=4,-1,0
  4805.0    0.07       0  5013.3    0.07       0  5022.4    0.07       0
  5501.9   0.035       0
Bank Sta=5013.3,5022.4
Exp/Cntr=0.3,0.1

Chan Stop Cuts=-1