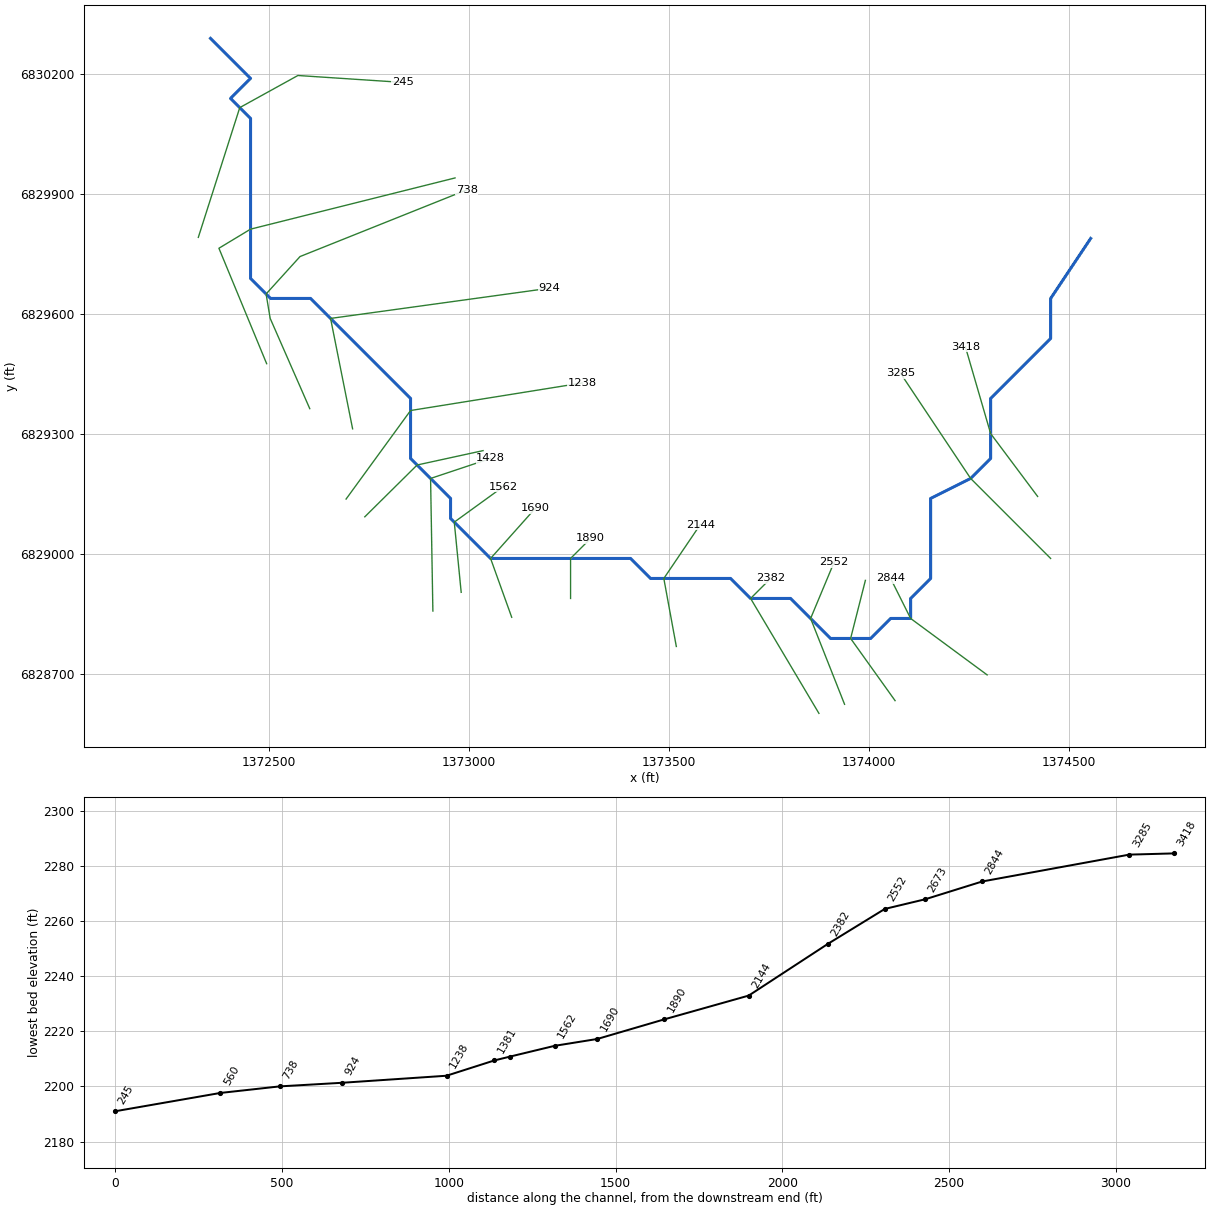
--- Sweetwater Creek Trib 12_5.prj (project) ---

Proj Title=Sweetwater Creek Trib 12_5 Base Level Engineering
Current Plan=p01
Default Exp/Contr=0.3,0.1
English Units
Geom File=g01
Flow File=f01
Plan File=p01
Y Axis Title=Elevation
X Axis Title(PF)=Main Channel Distance
X Axis Title(XS)=Station
BEGIN DESCRIPTION:
Sweetwater Creek Trib 12_5
END DESCRIPTION:
DSS Export Rating Curves= 0
DSS Export Rating Curve Sorted= 0
DSS Export Volume Flow Curves= 0
DXF OffsetX= 0
DXF OffsetY= 0
DXF ScaleX= 1
DXF ScaleY= 10

--- Sweetwater Creek Trib 12_5.p01 (plan) ---

Plan Title=Multiple Run
Short Identifier=Multiple
Geom File=g01
Flow File=f01
Subcritical Flow
K Sum by GR= 0
Std Step Tol= 0.01
Critical Tol= 0.01
Num of Std Step Trials= 20
Max Error Tol= 0.3
Flow Tol Ratio= 0.001
Split Flow NTrial= 30
Split Flow Tol= 0.02
Split Flow Ratio= 0.02
Log Output Level= 0
Friction Slope Method= 1
Unsteady Friction Slope Method= 2
Unsteady Bridges Friction Slope Method= 1
Parabolic Critical Depth
Global Vel Dist=  1 , 1 , 1
Global Log Level= 0
CheckData=True
Encroach Param= -1, 0, 0, 0
BEGIN DESCRIPTION:
Multiple Run
END DESCRIPTION:

--- Sweetwater Creek Trib 12_5.f01 (steady flow) ---

Flow Title=Multiple
Number of Profiles=7
Profile Names=10-year,25-year,50-year,1pct_min,100-year,1pct_plu,500-year
River Rch & RM= Sweetwater Creek,Reach-1,3418
      89     118     141      85     169     338     244
Boundary for River Rch & Prof#=Sweetwater Creek,Reach-1,1
Up Type=0
Dn Type=3
Dn Slope=0.005
Boundary for River Rch & Prof#=Sweetwater Creek,Reach-1,2
Up Type=0
Dn Type=3
Dn Slope=0.005
Boundary for River Rch & Prof#=Sweetwater Creek,Reach-1,3
Up Type=0
Dn Type=3
Dn Slope=0.005
Boundary for River Rch & Prof#=Sweetwater Creek,Reach-1,4
Up Type=0
Dn Type=3
Dn Slope=0.005
Boundary for River Rch & Prof#=Sweetwater Creek,Reach-1,5
Up Type=0
Dn Type=3
Dn Slope=0.005
Boundary for River Rch & Prof#=Sweetwater Creek,Reach-1,6
Up Type=0
Dn Type=3
Dn Slope=0.005
Boundary for River Rch & Prof#=Sweetwater Creek,Reach-1,7
Up Type=0
Dn Type=3
Dn Slope=0.005

--- Sweetwater Creek Trib 12_5.g01 (geometry) ---

Geom Title=Existing Conditions
Program Version=4.10

River Reach=Sweetwater Creek,Reach-1
Reach XY= 30
        1374555.        6829788.        1374455.        6829638.
        1374455.        6829538.        1374305.        6829388.
        1374305.        6829238.        1374255.        6829188.
        1374155.        6829138.        1374155.        6828938.
        1374105.        6828888.        1374105.        6828838.
        1374055.        6828838.        1374005.        6828788.
        1373905.        6828788.        1373805.        6828888.
        1373705.        6828888.        1373655.        6828938.
        1373455.        6828938.        1373405.        6828988.
        1373055.        6828988.        1372955.        6829088.
        1372955.        6829138.        1372855.        6829238.
        1372855.        6829388.        1372605.        6829638.
        1372505.        6829638.        1372455.        6829688.
        1372455.        6830088.        1372405.        6830138.
        1372455.        6830188.      1372354.86      6830288.16

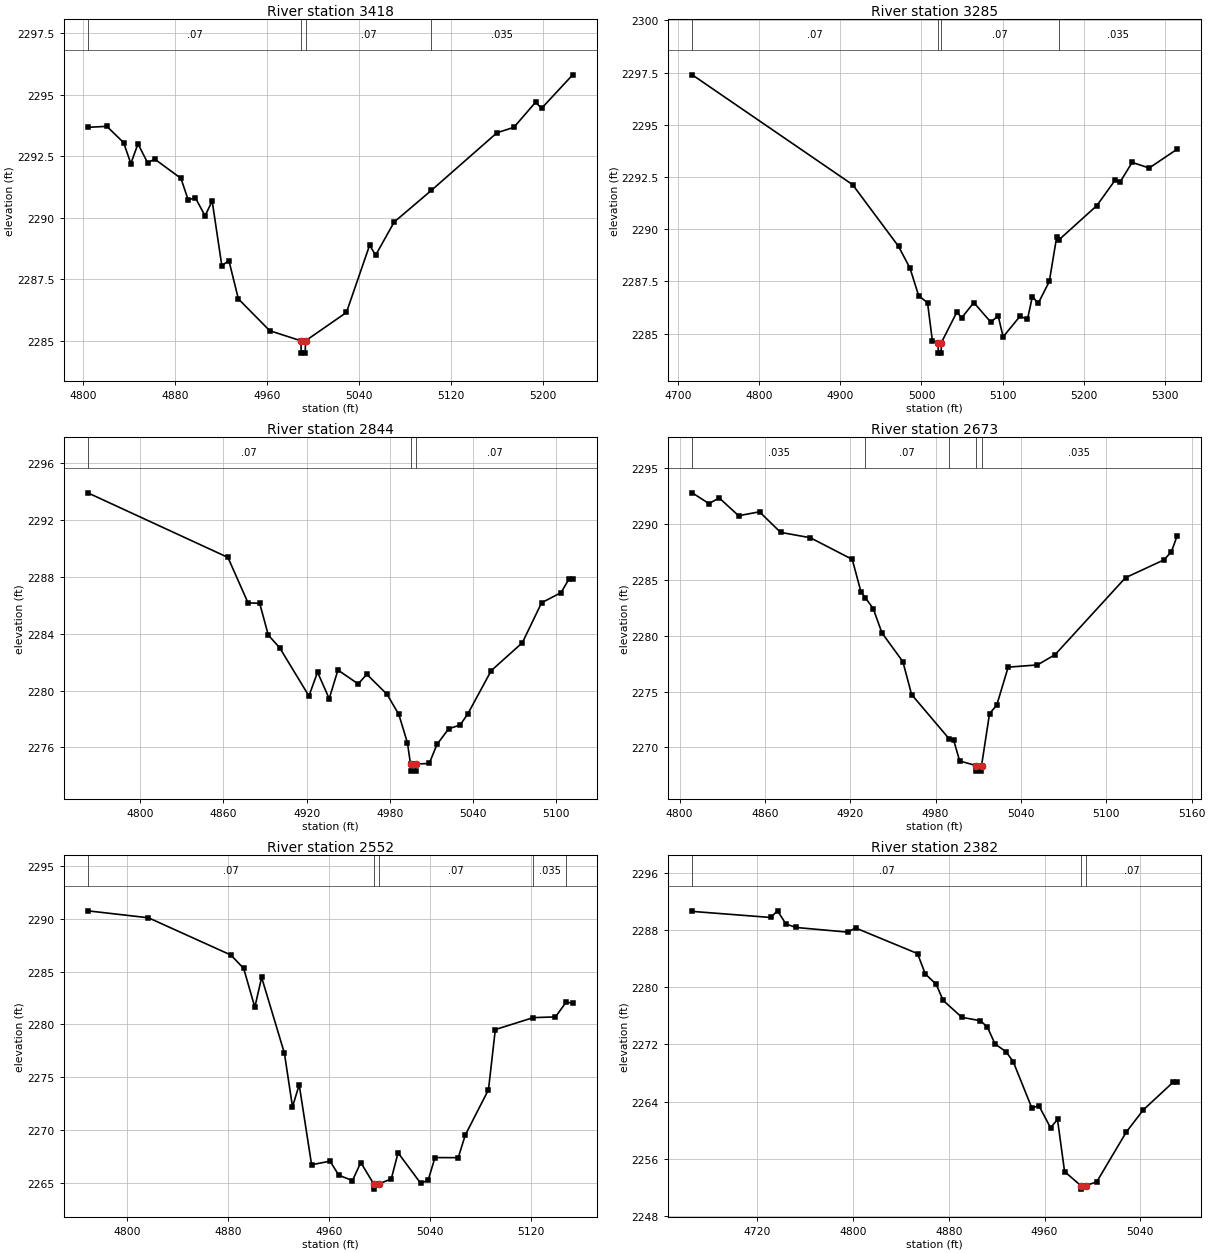
Type RM Length L Ch R = 1 ,3418    ,133,133,133
BEGIN DESCRIPTION:
Sweetwater Creek Trib 12_5 4369
END DESCRIPTION:
XS GIS Cut Line= 3
      1374422.46      6829143.01        1374305.      6829300.17
      1374241.87      6829517.17
#Sta/Elev= 30
  4803.8 2293.67  4820.4 2293.71    4835 2293.05  4841.3  2292.2  4847.5    2293
  4855.9 2292.23  4862.1 2292.38  4884.9  2291.6  4891.2 2290.73  4897.5 2290.81
  4905.9 2290.08  4912.1 2290.68  4920.5 2288.06  4926.7 2288.26  4934.9 2286.71
  4962.2 2285.42  4989.4 2285.01  4989.6 2284.51  4993.1 2284.51  4993.4 2285.01
    5029 2286.16  5049.2 2288.89  5054.4 2288.48  5070.6 2289.83  5102.9 2291.11
  5160.1 2293.45  5174.8 2293.67  5193.7 2294.69  5198.9 2294.44    5226  2295.8
#Mann= 4 ,-1 , 0
  4803.8     .07       0  4989.4     .07       0  4993.4     .07       0
  5102.9    .035       0
Bank Sta=4989.4,4993.4
XS Rating Curve= 0 ,0
Exp/Cntr=0.3,0.1

Type RM Length L Ch R = 1 ,3285    ,441,441,441
BEGIN DESCRIPTION:
Sweetwater Creek Trib 12.5 5.0
END DESCRIPTION:
XS GIS Cut Line= 3
      1374454.97      6828988.03        1374255.        6829188.
      1374080.04      6829450.43
#Sta/Elev= 30
  4717.2 2297.39  4915.1 2292.13  4971.7 2289.18  4985.9 2288.13  4996.5 2286.82
  5007.5 2286.48  5013.5 2284.64  5020.5 2284.57  5020.8 2284.07  5024.3 2284.07
  5024.5 2284.57  5043.6 2286.03  5049.6 2285.76  5064.6 2286.49  5085.6 2285.55
  5094.6 2285.86  5100.7 2284.85  5121.7 2285.84  5130.7 2285.68  5136.7 2286.76
  5144.2 2286.47  5157.7  2287.5  5166.8 2289.63  5169.8  2289.5  5216.3 2291.13
  5238.9 2292.35  5244.9 2292.25  5259.9  2293.2  5280.9 2292.93  5315.4 2293.83
#Mann= 4 ,-1 , 0
  4717.2     .07       0  5020.5     .07       0  5024.5     .07       0
  5169.8    .035       0
Bank Sta=5020.5,5024.5
XS Rating Curve= 0 ,0
Exp/Cntr=0.3,0.1

Type RM Length L Ch R = 1 ,2844    ,171,171,171
BEGIN DESCRIPTION:
Sweetwater Creek Trib 12.5 4.0
END DESCRIPTION:
XS GIS Cut Line= 3
       1374296.3      6828696.91        1374105.        6828838.
        1374055.        6828938.
#Sta/Elev= 30
  4762.3 2293.93  4863.3 2289.38  4877.8 2286.18  4886.2 2286.15  4892.4 2283.91
  4900.6 2283.02  4921.7 2279.62  4927.9  2281.3  4936.3 2279.43  4942.6 2281.45
  4957.2 2280.47  4963.4 2281.15    4978 2279.74  4986.5 2278.32  4992.7 2276.32
  4994.9 2274.83  4995.1 2274.33  4998.6 2274.33  4998.9 2274.83  5008.4 2274.87
    5014 2276.21  5022.4 2277.31  5030.7 2277.58  5036.3 2278.38  5053.1 2281.41
  5075.5 2283.37  5089.4 2286.19  5103.4  2286.9    5109 2287.84  5111.8 2287.84
#Mann= 3 ,-1 , 0
  4762.3     .07       0  4994.9     .07       0  4998.9     .07       0
Bank Sta=4994.9,4998.9
XS Rating Curve= 0 ,0
Exp/Cntr=0.3,0.1

Type RM Length L Ch R = 1 ,2673    ,121,121,121
BEGIN DESCRIPTION:
Sweetwater Creek Trib 12.5 4158
END DESCRIPTION:
XS GIS Cut Line= 3
      1374066.16      6828632.56        1373955.        6828788.
      1373991.92      6828933.18
#Sta/Elev= 30
  4808.9  2292.8  4820.6 2291.84  4827.9 2292.34  4841.5 2290.75  4856.2  2291.1
    4871 2289.26  4891.9 2288.78  4921.4 2286.84  4927.5 2283.94  4930.5 2283.42
  4936.1 2282.44  4942.3 2280.25    4957 2277.68  4963.1 2274.74  4989.6 2270.76
  4992.6 2270.69  4996.9 2268.79  5008.3 2268.38  5008.6 2267.88  5012.1 2267.88
  5012.3 2268.38  5017.9 2273.02    5023  2273.8    5031 2277.19  5051.6 2277.39
    5064 2278.31  5113.5  2285.2  5140.6  2286.8  5145.8 2287.53  5149.8 2288.95
#Mann= 5 ,-1 , 0
  4808.9    .035       0  4930.5     .07       0  4989.6    .035       0
  5008.3    .035       0  5012.3    .035       0
Bank Sta=5008.3,5012.3
XS Rating Curve= 0 ,0
Exp/Cntr=0.3,0.1

Type RM Length L Ch R = 1 ,2552    ,170,170,170
BEGIN DESCRIPTION:
Sweetwater Creek Trib 12.5 4159
END DESCRIPTION:
XS GIS Cut Line= 3
      1373939.89      6828623.38        1373855.        6828838.
      1373913.84      6828978.91
#Sta/Elev= 30
  4769.2 2290.75  4817.2 2290.09  4882.4 2286.56  4892.5 2285.29  4901.3 2281.62
  4906.7 2284.44  4924.7 2277.26  4931.1 2272.18  4936.4 2274.27  4946.2 2266.69
  4960.8 2267.03  4967.7  2265.7  4978.5 2265.19  4985.1  2266.9  4995.3 2264.88
  4995.6 2264.38  4999.3 2264.88  5009.2 2265.34  5014.6 2267.82  5032.5 2264.93
  5038.4 2265.23  5043.8 2267.37  5062.2 2267.36  5067.7 2269.49  5086.1  2273.8
  5091.5  2279.5  5121.5 2280.63  5139.1  2280.7  5147.4 2282.08  5152.7 2282.02
#Mann= 5 ,-1 , 0
  4769.2     .07       0  4995.3     .07       0  4999.3     .07       0
  5121.5    .035       0  5147.4     .07       0
Bank Sta=4995.3,4999.3
XS Rating Curve= 0 ,0
Exp/Cntr=0.3,0.1

Type RM Length L Ch R = 1 ,2382    ,238,238,238
BEGIN DESCRIPTION:
Sweetwater Creek Trib 12.5 3.0
END DESCRIPTION:
XS GIS Cut Line= 3
      1373875.79      6828600.73        1373705.        6828888.
      1373754.99      6828937.99
#Sta/Elev= 30
  4665.8 2290.62  4731.2 2289.77    4737  2290.7  4744.1 2288.85  4752.6 2288.37
  4795.5 2287.72  4802.2  2288.3  4853.9 2284.72  4860.4 2281.87  4869.5 2280.42
  4875.3 2278.17  4890.9  2275.8  4906.5 2275.32  4912.3 2274.42  4918.6 2272.08
  4927.9 2270.97  4933.8  2269.6  4949.4  2263.1  4955.2 2263.45    4965 2260.34
  4970.8 2261.51  4976.7 2254.22  4990.2 2252.26  4990.4 2251.76  4994.2 2252.26
  5003.5 2252.76  5028.3 2259.76  5042.4 2262.84  5067.2  2266.7  5070.7  2266.7
#Mann= 3 ,-1 , 0
  4665.8     .07       0  4990.2     .07       0  4994.2     .07       0
Bank Sta=4990.2,4994.2
XS Rating Curve= 0 ,0
Exp/Cntr=0.3,0.1

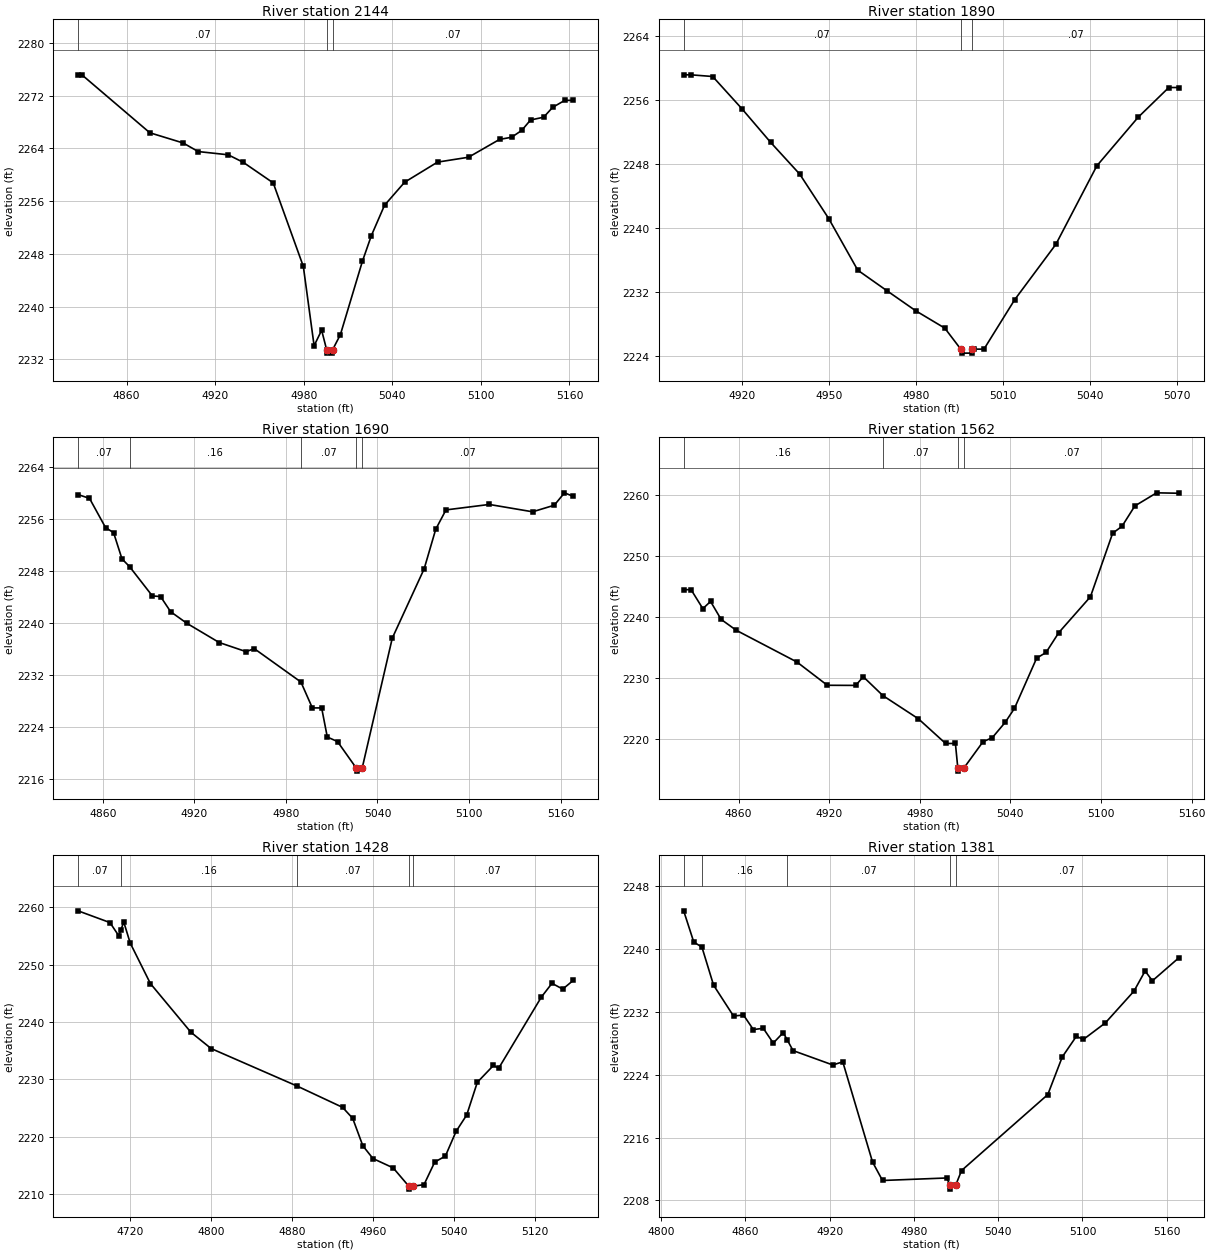
Type RM Length L Ch R = 1 ,2144    ,254,254,254
BEGIN DESCRIPTION:
Sweetwater Creek Trib 12_5 4158
END DESCRIPTION:
XS GIS Cut Line= 3
       1373519.3      6828767.95      1373488.05        6828938.
       1373579.2      6829072.65
#Sta/Elev= 30
  4827.1 2275.14  4829.7 2275.14  4875.7 2266.36  4898.3 2264.81  4908.5 2263.51
  4928.8 2263.02    4939 2261.88  4959.3 2258.76  4979.7  2246.1    4987 2234.08
  4992.1 2236.43  4995.5 2233.46  4995.7 2232.96  4999.2 2232.96  4999.5 2233.46
  5004.8 2235.76  5019.7 2246.87  5025.8 2250.78  5034.7 2255.37  5048.3 2258.86
  5070.6 2261.91  5091.6 2262.65  5112.6 2265.35  5120.8 2265.68  5127.6 2266.71
  5133.6 2268.29  5142.5 2268.72  5148.6 2270.21  5156.8 2271.27  5162.6 2271.27
#Mann= 3 ,-1 , 0
  4827.1     .07       0  4995.5     .07       0  4999.5     .07       0
Bank Sta=4995.5,4999.5
XS Rating Curve= 0 ,0
Exp/Cntr=0.3,0.1

Type RM Length L Ch R = 1 ,1890    ,200,200,200
BEGIN DESCRIPTION:
Sweetwater Creek Trib 12.5 2.0
END DESCRIPTION:
XS GIS Cut Line= 3
        1373255.        6828888.        1373255.        6828988.
      1373304.99      6829037.99
#Sta/Elev= 23
    4900 2259.17  4902.5 2259.17    4910 2258.96    4920 2254.95    4930  2250.7
    4940 2246.73    4950 2241.16    4960  2234.7    4970 2232.14    4980 2229.61
    4990 2227.44  4995.5 2224.81  4995.8 2224.31  4999.3 2224.31  4999.5 2224.81
    5000 2224.81  5003.5 2224.81  5014.1 2231.01  5028.3 2237.95  5042.4 2247.77
  5056.6 2253.84  5067.2 2257.58  5070.7 2257.58
#Mann= 3 ,-1 , 0
    4900     .07       0  4995.5     .07       0  4999.5     .07       0
Bank Sta=4995.5,4999.5
XS Rating Curve= 0 ,0
Exp/Cntr=0.3,0.1

Type RM Length L Ch R = 1 ,1690    ,128,128,128
BEGIN DESCRIPTION:
Sweetwater Creek Trib 12_5 4159
END DESCRIPTION:
XS GIS Cut Line= 3
      1373107.83       6828840.9        1373055.        6828988.
      1373167.14      6829113.63
#Sta/Elev= 30
  4843.7  2259.8  4851.2 2259.22  4861.7 2254.73    4867 2253.93  4872.5  2249.9
  4877.5  2248.7  4892.4  2244.2  4897.8  2244.1  4904.4 2241.77    4915 2239.99
  4936.2 2237.03  4953.9 2235.62  4959.2 2236.09  4989.8 2230.95  4997.3 2226.96
  5003.4 2226.96  5007.1 2222.48  5013.8 2221.78    5026 2217.73  5026.3 2217.23
    5030 2217.73  5049.7  2237.7  5070.6 2248.37  5078.2 2254.47  5084.9 2257.44
  5113.3 2258.28  5141.7 2257.15  5155.9 2258.16  5162.6 2260.07  5168.4 2259.52
#Mann= 5 ,-1 , 0
  4843.7     .07       0  4877.5     .16       0  4989.8     .07       0
    5026     .07       0    5030     .07       0
Bank Sta=5026,5030
XS Rating Curve= 0 ,0
Exp/Cntr=0.3,0.1

Type RM Length L Ch R = 1 ,1562    ,134,134,134
BEGIN DESCRIPTION:
Sweetwater Creek Trib 12_5 4162
END DESCRIPTION:
XS GIS Cut Line= 3
      1372981.54      6828903.32      1372964.23      6829078.77
      1373087.01      6829167.69
#Sta/Elev= 30
  4823.7 2244.46  4828.6 2244.46  4836.4 2241.35  4841.5 2242.53  4848.5 2239.59
  4858.5 2237.81  4898.7 2232.61  4918.8  2228.8  4937.6 2228.78  4942.6  2230.2
  4955.6 2227.11  4979.1 2223.31  4997.1 2219.27  5003.6 2219.27  5005.2 2215.24
  5005.4 2214.74  5009.2 2215.24  5021.9 2219.56    5028 2220.21  5036.6 2222.74
  5042.7 2225.02  5057.4 2233.25  5063.6 2234.17  5072.1 2237.44    5093  2243.3
  5107.7  2253.7  5113.9 2254.84  5122.4 2258.17  5136.8 2260.32  5151.6 2260.25
#Mann= 4 ,-1 , 0
  4823.7     .16       0  4955.6     .07       0  5005.2     .07       0
  5009.2     .07       0
Bank Sta=5005.2,5009.2
XS Rating Curve= 0 ,0
Exp/Cntr=0.3,0.1

Type RM Length L Ch R = 1 ,1428    ,47,47,47
BEGIN DESCRIPTION:
Sweetwater Creek Trib 12.5 1.0
END DESCRIPTION:
XS GIS Cut Line= 3
      1372910.76      6828856.55        1372905.        6829188.
      1373054.99        6829238.
#Sta/Elev= 30
  4668.5  2259.4    4700 2257.35  4708.7 2255.06  4710.7 2256.01  4713.7 2257.44
    4720  2253.8    4740 2246.71    4780 2238.22    4800 2235.37    4885 2228.82
    4930  2225.1    4940 2223.18    4950  2218.4    4960 2216.17    4980 2214.54
  4995.5 2211.33  4995.7 2210.83  4999.5 2211.33  5010.5 2211.62  5021.1 2215.56
  5031.6 2216.59  5042.2 2220.91  5052.7 2223.77  5063.2 2229.48  5079.1 2232.41
  5084.3 2231.93  5126.5 2244.35    5137 2246.75  5147.6 2245.74  5158.1 2247.27
#Mann= 5 ,-1 , 0
  4668.5     .07       0  4710.7     .16       0    4885     .07       0
  4995.5     .07       0  4999.5     .07       0
Bank Sta=4995.5,4999.5
XS Rating Curve= 0 ,0
Exp/Cntr=0.3,0.1

Type RM Length L Ch R = 1 ,1381    ,143,143,143
BEGIN DESCRIPTION:
Sweetwater Creek Trib 12_5 4160
END DESCRIPTION:
XS GIS Cut Line= 3
      1372740.64      6829092.15      1372871.39      6829221.61
      1373036.22      6829257.53
#Sta/Elev= 30
    4816 2244.87  4823.2 2240.89    4829 2240.25  4837.3  2235.4  4851.5 2231.47
  4858.6  2231.6  4865.6 2229.75  4872.7 2229.91  4879.8 2228.03  4886.9 2229.36
  4889.9 2228.38  4893.9 2227.07  4922.2 2225.24  4929.3 2225.64  4950.5 2212.88
  4957.6 2210.53  5003.3 2210.85  5005.7 2209.93  5005.9 2209.43  5009.7 2209.93
  5013.9  2211.8  5075.3 2221.47  5085.6 2226.26  5095.6 2228.88  5100.7  2228.5
  5116.3  2230.6  5136.7 2234.65  5144.6 2237.21  5149.8 2235.96  5168.7  2238.9
#Mann= 5 ,-1 , 0
    4816     .07       0    4829     .16       0  4889.9     .07       0
  5005.7     .07       0  5009.7     .07       0
Bank Sta=5005.7,5009.7
XS Rating Curve= 0 ,0
Exp/Cntr=0.3,0.1

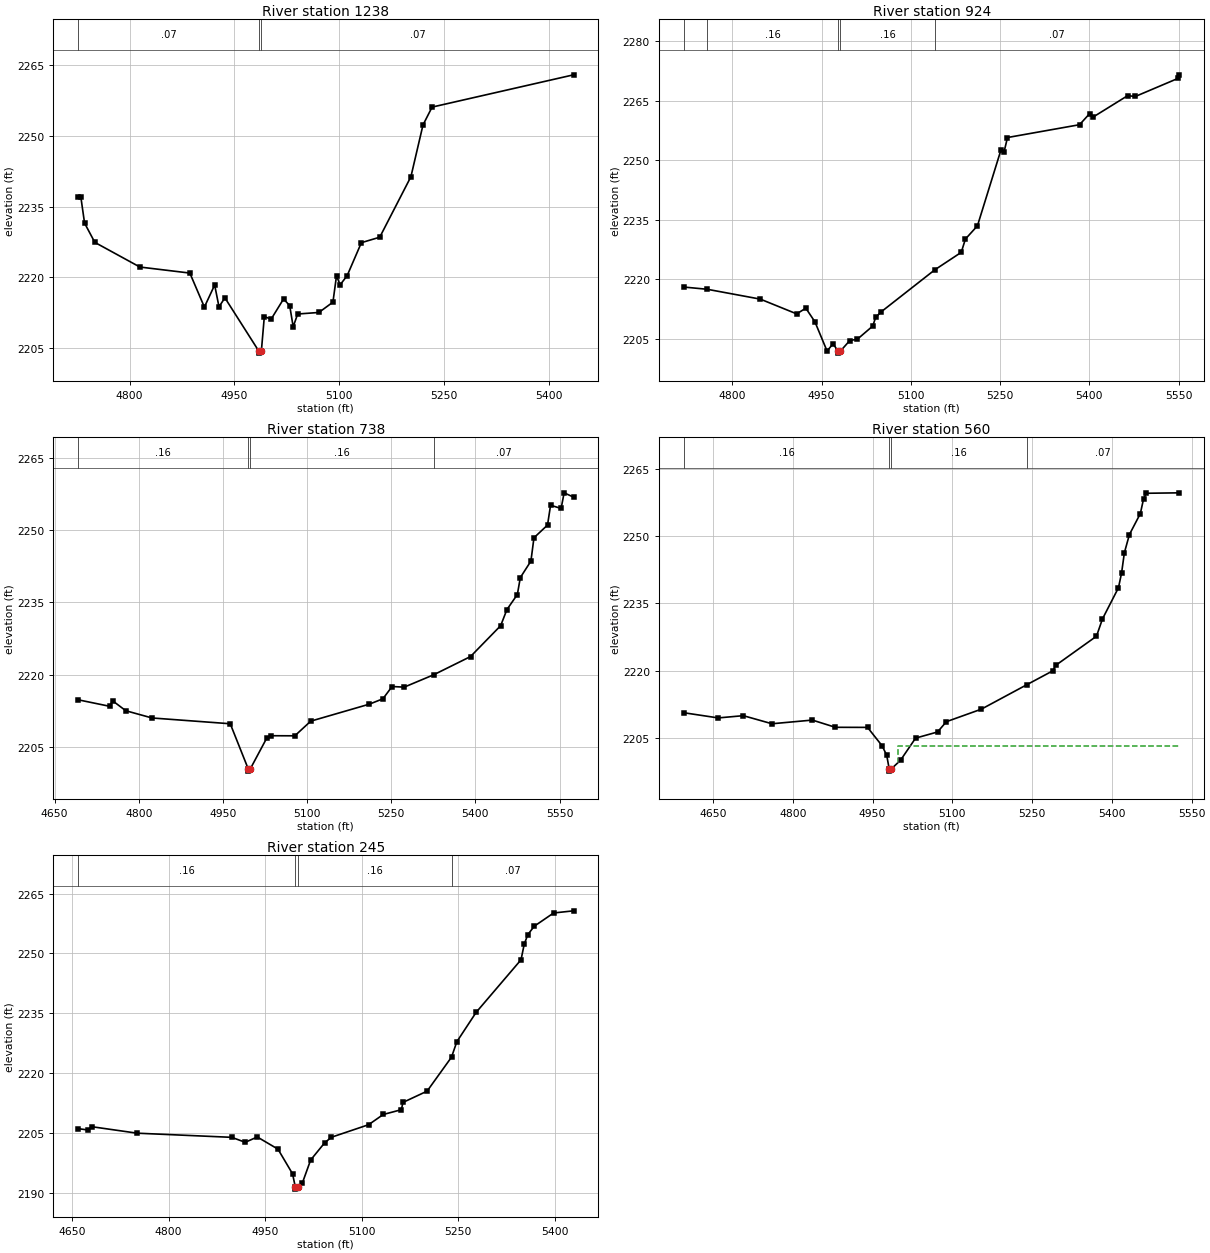
Type RM Length L Ch R = 1 ,1238    ,314,314,314
BEGIN DESCRIPTION:
Sweetwater Creek Trib 12_5 4161
END DESCRIPTION:
XS GIS Cut Line= 3
       1372693.8      6829136.47        1372855.      6829357.79
       1373284.9       6829426.8
#Sta/Elev= 30
  4726.2 2237.01  4730.2 2237.01  4735.5 2231.49  4750.2  2227.4  4814.7 2222.17
  4886.2 2220.89    4907 2213.67  4921.7 2218.36  4927.9 2213.74  4936.4 2215.63
  4984.6  2204.4  4984.9  2203.9  4988.6  2204.4  4992.8 2211.67  5002.5  2211.1
  5020.3 2215.39  5029.1 2213.99  5034.1 2209.49  5040.5  2212.2  5070.9 2212.53
    5091 2214.72  5096.1  2220.3  5101.3 2218.39  5111.4 2220.36  5131.7 2227.34
    5158  2228.5  5202.6 2241.34  5219.9 2252.32  5232.9 2256.11  5435.4 2262.96
#Mann= 3 ,-1 , 0
  4726.2     .07       0  4984.6     .07       0  4988.6     .07       0
Bank Sta=4984.6,4988.6
XS Rating Curve= 0 ,0
Exp/Cntr=0.3,0.1

Type RM Length L Ch R = 1 ,924     ,186,186,186
BEGIN DESCRIPTION:
Sweetwater Creek Trib 12_5 4370
END DESCRIPTION:
XS GIS Cut Line= 3
      1372710.11      6829312.05        1372655.        6829588.
      1373201.32       6829663.4
#Sta/Elev= 30
  4718.6 2217.99  4757.8 2217.43    4847 2214.95  4908.2 2211.23  4923.5 2212.67
  4938.8 2209.24  4959.2 2201.88  4969.4  2203.7  4977.6 2201.84  4977.9 2201.34
  4981.6 2201.84  4997.5 2204.52  5010.1 2204.84    5036 2208.16    5041 2210.38
  5050.5 2211.78  5140.4 2222.34  5184.8 2226.74  5191.8 2230.09    5212 2233.42
  5251.7 2252.62  5256.7 2252.01  5262.5 2255.67  5383.6  2258.9  5400.5 2261.67
  5405.6 2260.75  5464.4 2266.21  5477.5 2266.02  5549.4 2270.59  5551.5 2271.47
#Mann= 5 ,-1 , 0
  4718.6     .07       0  4757.8     .16       0  4977.6     .07       0
  4981.6     .16       0  5140.4     .07       0
Bank Sta=4977.6,4981.6
XS Rating Curve= 0 ,0
Exp/Cntr=0.3,0.1

Type RM Length L Ch R = 1 ,738     ,178,178,178
BEGIN DESCRIPTION:
Sweetwater Creek Trib 12_5 4433
END DESCRIPTION:
XS GIS Cut Line= 5
      1372603.01      6829362.43      1372504.04      6829588.15
      1372493.85      6829649.15      1372578.69      6829742.67
      1372995.33      6829909.32
#Sta/Elev= 30
  4691.7 2214.83    4748 2213.48  4753.4 2214.61  4776.8 2212.56  4823.5 2211.06
    4963 2209.86  4994.9 2200.54  4995.1 2200.04  4998.9 2200.54  5028.1  2206.9
  5035.6 2207.38  5078.1 2207.36  5106.5  2210.4  5210.9 2213.92  5235.1 2215.03
  5251.5 2217.58  5273.1 2217.45  5325.8 2220.02  5391.3 2223.79  5445.1  2230.2
  5456.2 2233.53  5474.8 2236.65  5480.1 2240.16    5499 2243.58  5504.4 2248.41
  5528.6 2251.05    5534 2255.16  5552.8 2254.49  5558.2 2257.73    5575 2256.84
#Mann= 4 ,-1 , 0
  4691.7     .16       0  4994.9     .07       0  4998.9     .16       0
  5325.8     .07       0
Bank Sta=4994.9,4998.9
XS Rating Curve= 0 ,0
Exp/Cntr=0.3,0.1

Type RM Length L Ch R = 1 ,560     ,315,315,315
BEGIN DESCRIPTION:
Sweetwater Creek Trib 12_5 4371
END DESCRIPTION:
XS GIS Cut Line= 4
      1372495.26       6829474.8      1372375.91      6829763.42
        1372455.      6829811.16      1372966.21       6829939.2
#Sta/Elev= 30
  4595.3 2210.66  4659.8 2209.51    4707 2210.01  4760.9 2208.21  4836.8 2209.03
  4880.1 2207.42  4940.6  2207.4  4967.8 2203.33  4976.6 2201.21  4981.3 2198.16
  4981.6 2197.66  4985.3 2198.16  5002.6 2200.08  5030.9 2205.01  5072.2 2206.38
  5088.8 2208.67  5154.6 2211.46  5239.7 2216.88  5288.6 2219.98  5294.7 2221.24
  5371.1 2227.71  5382.3 2231.55  5412.4  2238.5  5418.3 2241.81  5423.5 2246.28
    5433 2250.35  5453.6 2255.03  5459.5 2258.24  5464.7 2259.54    5527 2259.64
#Mann= 4 ,-1 , 0
  4595.3     .16       0  4981.3     .07       0  4985.3     .16       0
  5239.7     .07       0
#XS Ineff= 2 , 0
                         4997.62          2203.3
Permanent Ineff=
       F       F
Bank Sta=4981.3,4985.3
XS Rating Curve= 0 ,0
Exp/Cntr=0.3,0.1

Type RM Length L Ch R = 1 ,245     ,0,0,0
BEGIN DESCRIPTION:
Sweetwater Creek Trib 12_5 4372
END DESCRIPTION:
XS GIS Cut Line= 4
      1372324.42      6829790.63      1372428.01      6830114.99
      1372573.39      6830195.28      1372835.94      6830177.92
#Sta/Elev= 30
  4659.5 2206.17  4675.2 2205.82  4680.4 2206.66  4751.2 2205.03  4898.2 2203.99
  4919.2 2202.75  4937.9 2204.08    4970 2201.04  4992.7 2194.86    4997 2191.53
  4997.2 2191.03    5001 2191.53    5008  2192.6  5020.8 2198.32  5042.6 2202.63
    5053 2204.01  5110.8 2207.15  5133.6 2209.71  5161.8 2210.91  5164.1 2212.72
  5201.7 2215.55  5239.6 2224.05  5247.9 2227.92  5277.9 2235.27  5347.6 2248.42
  5352.6 2252.33  5358.1  2254.7  5368.1 2256.81  5398.2 2260.13  5429.2 2260.67
#Mann= 4 ,-1 , 0
  4659.5     .16       0    4997     .07       0    5001     .16       0
  5239.6     .07       0
Bank Sta=4997,5001
XS Rating Curve= 0 ,0
Exp/Cntr=0.3,0.1

Chan Stop Cuts=-1
Use User Specified Reach Order=0
Composite Channel Slope=5