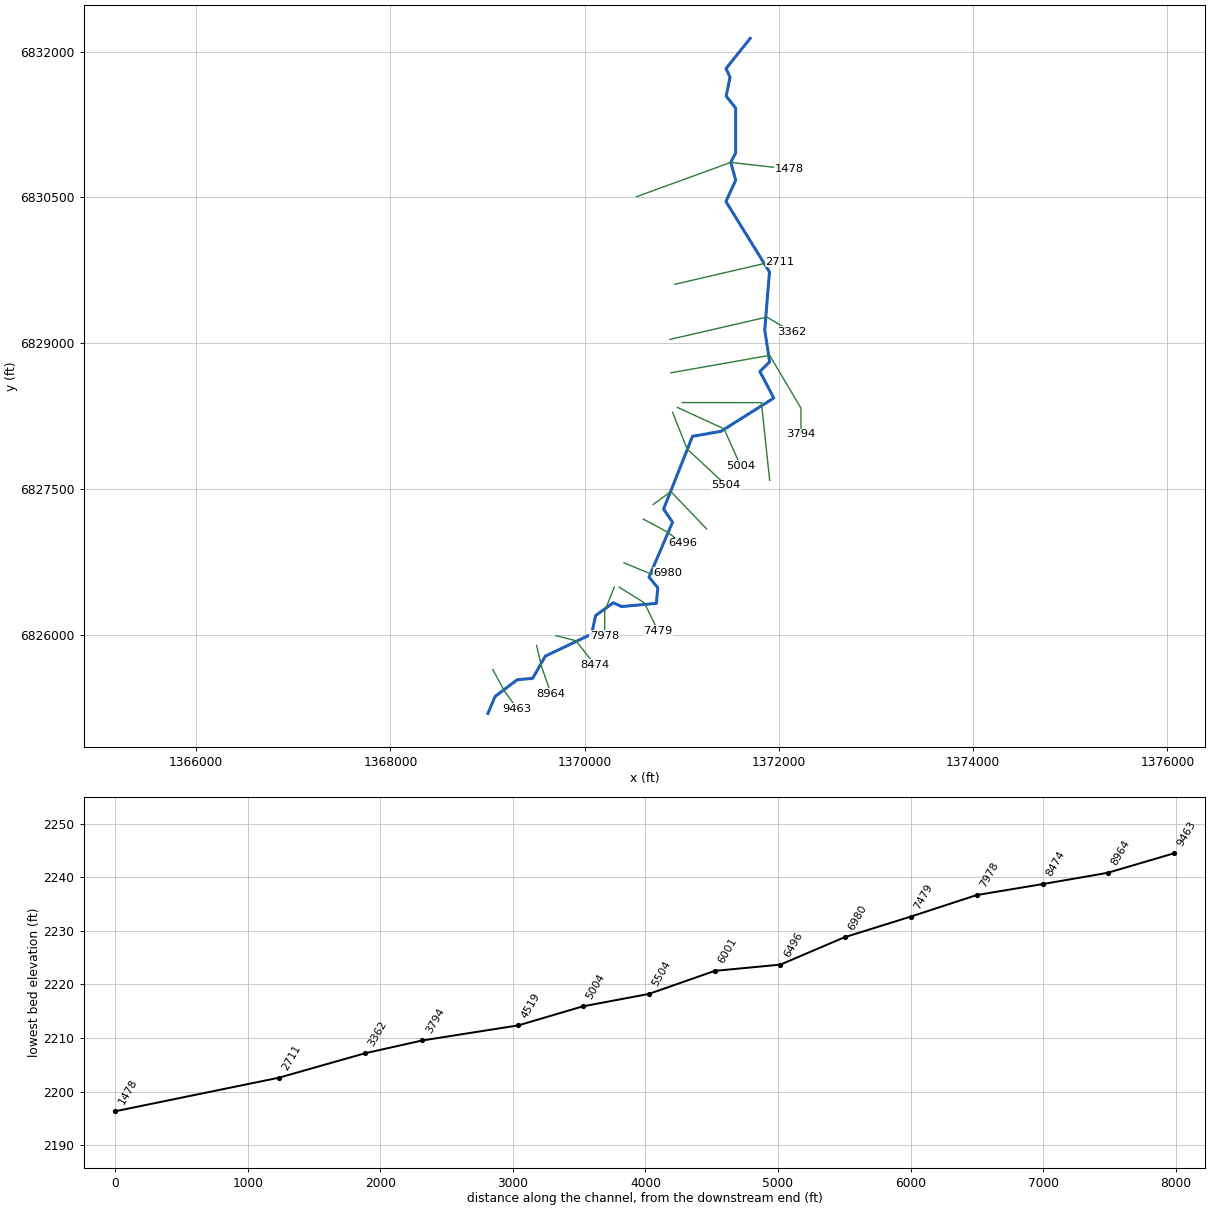
--- Sweetwater Creek Trib 13.prj (project) ---

Proj Title=Sweetwater Creek Trib 13 Base Level Engineering
Current Plan=p01
Default Exp/Contr=0.3,0.1
English Units
Geom File=g01
Flow File=f01
Plan File=p01
Y Axis Title=Elevation
X Axis Title(PF)=Main Channel Distance
X Axis Title(XS)=Station
BEGIN DESCRIPTION:
Sweetwater Creek Trib 13
END DESCRIPTION:
DSS Export Rating Curves= 0
DSS Export Rating Curve Sorted= 0
DSS Export Volume Flow Curves= 0
DXF OffsetX= 0
DXF OffsetY= 0
DXF ScaleX= 1
DXF ScaleY= 10

--- Sweetwater Creek Trib 13.p01 (plan) ---

Plan Title=Multiple Run
Short Identifier=Multiple
Geom File=g01
Flow File=f01
Subcritical Flow
K Sum by GR= 0
Std Step Tol= 0.01
Critical Tol= 0.01
Num of Std Step Trials= 20
Max Error Tol= 0.3
Flow Tol Ratio= 0.001
Split Flow NTrial= 30
Split Flow Tol= 0.02
Split Flow Ratio= 0.02
Log Output Level= 0
Friction Slope Method= 1
Unsteady Friction Slope Method= 2
Unsteady Bridges Friction Slope Method= 1
Parabolic Critical Depth
Global Vel Dist=  1 , 1 , 1
Global Log Level= 0
CheckData=True
Encroach Param= -1, 0, 0, 0
BEGIN DESCRIPTION:
Multiple Run
END DESCRIPTION:

--- Sweetwater Creek Trib 13.f01 (steady flow) ---

Flow Title=Multiple
Number of Profiles=7
Profile Names=10-year,25-year,50-year,1pct_min,100-year,1pct_plu,500-year
River Rch & RM= Sweetwater Creek,Reach-1,9463
     335     486     615     388     774    1545    1241
River Rch & RM= Sweetwater Creek,Reach-1,7978
     395     573     726     457     912    1819    1459
Boundary for River Rch & Prof#=Sweetwater Creek,Reach-1,1
Up Type=0
Dn Type=3
Dn Slope=0.005
Boundary for River Rch & Prof#=Sweetwater Creek,Reach-1,2
Up Type=0
Dn Type=3
Dn Slope=0.005
Boundary for River Rch & Prof#=Sweetwater Creek,Reach-1,3
Up Type=0
Dn Type=3
Dn Slope=0.005
Boundary for River Rch & Prof#=Sweetwater Creek,Reach-1,4
Up Type=0
Dn Type=3
Dn Slope=0.005
Boundary for River Rch & Prof#=Sweetwater Creek,Reach-1,5
Up Type=0
Dn Type=3
Dn Slope=0.005
Boundary for River Rch & Prof#=Sweetwater Creek,Reach-1,6
Up Type=0
Dn Type=3
Dn Slope=0.005
Boundary for River Rch & Prof#=Sweetwater Creek,Reach-1,7
Up Type=0
Dn Type=3
Dn Slope=0.005

--- Sweetwater Creek Trib 13.g01 (geometry) ---

Geom Title=Existing Conditions

River Reach=Sweetwater Creek,Reach-1
Reach XY= 30
      1369005.00      6825188.00      1369077.72      6825361.90
      1369306.47      6825534.46      1369464.82      6825548.47
      1369594.94      6825777.39      1370072.14      6826004.45
      1370112.70      6826194.47      1370294.96      6826326.87
      1370380.00      6826287.78      1370738.73      6826320.69
      1370752.94      6826482.14      1370662.84      6826591.23
      1370905.24      6827156.46      1370812.88      6827291.22
      1371110.71      6828040.59      1371403.45      6828091.75
      1371947.51      6828434.38      1371804.51      6828708.23
      1371904.94      6828808.20      1371854.22      6829133.44
      1371903.03      6829732.10      1371454.78      6830458.06
      1371555.55      6830677.81      1371504.62      6830860.81
      1371554.91      6830958.03      1371554.91      6831419.78
      1371457.17      6831543.45      1371497.41      6831738.01
      1371455.80      6831827.30      1371705.00      6832138.00

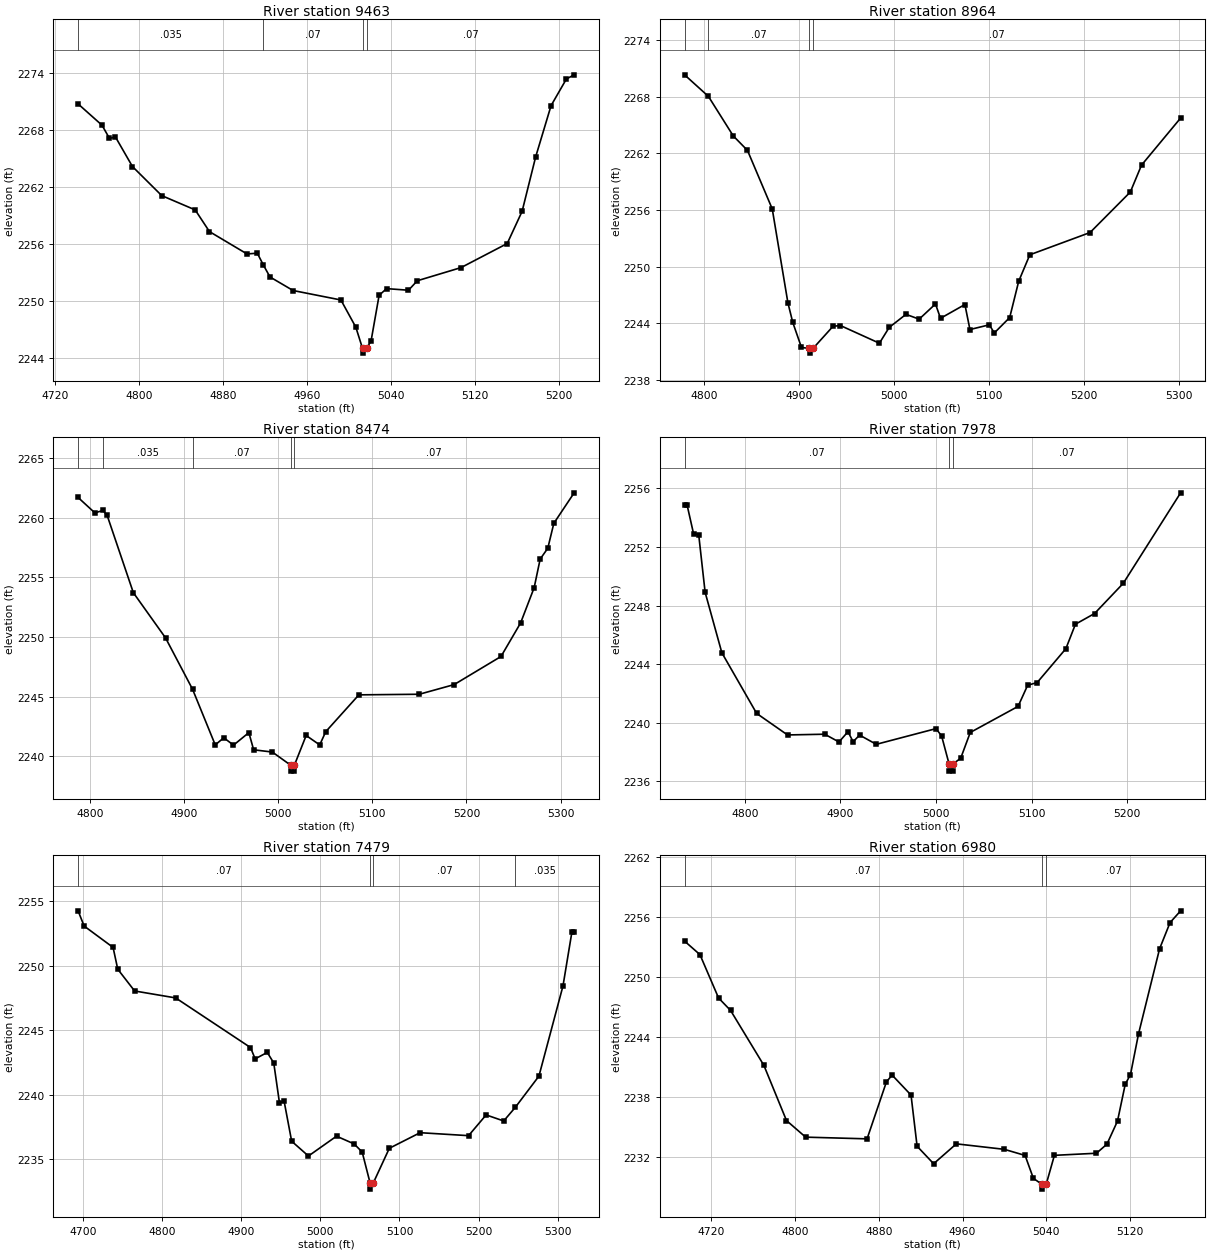
Type RM Length L Ch R = 1,9463,499,499,499
BEGIN DESCRIPTION:
Sweetwater Creek Trib 13 18.0
END DESCRIPTION:
XS GIS Cut Line= 3
      1369054.99      6825638.01      1369178.46      6825411.02
      1369305.03      6825237.97
#Sta/Elev= 30
  4741.6 2270.78  4764.4 2268.53  4771.5 2267.14  4777.2 2267.29  4793.4 2264.17
  4821.3 2261.10  4853.2 2259.59  4866.8 2257.30  4902.6 2254.94  4912.4 2255.02
  4918.3 2253.75  4924.5 2252.51  4946.5 2251.08  4992.1 2250.08  5006.3 2247.21
  5012.7 2244.97  5013.0 2244.47  5016.7 2244.97  5020.9 2245.79  5028.5 2250.57
  5035.6 2251.28  5056.5 2251.11  5064.9 2252.11  5106.6 2253.50  5150.6 2256.04
  5164.8 2259.44  5177.7 2265.18  5192.4 2270.60  5207.0 2273.41  5214.4 2273.85
#Mann=4,-1,0
  4741.6   0.035       0  4918.3    0.07       0  5012.7    0.07       0
  5016.7    0.07       0
Bank Sta=5012.7,5016.7
Exp/Cntr=0.3,0.1

Type RM Length L Ch R = 1,8964,490,490,490
BEGIN DESCRIPTION:
Sweetwater Creek Trib 13 17.0
END DESCRIPTION:
XS GIS Cut Line= 3
      1369505.01      6825887.95      1369555.19      6825672.93
      1369655.00      6825388.01
#Sta/Elev= 30
  4779.2 2270.33  4804.3 2268.05  4830.5 2263.86  4845.5 2262.32  4871.6 2256.12
  4888.1 2246.17  4893.2 2244.10  4902.4 2241.44  4910.6 2241.34  4910.9 2240.84
  4914.6 2241.34  4935.7 2243.69  4943.5 2243.76  4984.5 2241.89  4994.8 2243.56
  5012.5 2244.95  5026.4 2244.44  5043.6 2246.05  5048.9 2244.53  5074.6 2245.99
  5079.9 2243.34  5100.3 2243.84  5105.6 2242.98  5121.8 2244.61  5131.3 2248.46
  5143.0 2251.26  5206.5 2253.62  5248.9 2257.91  5260.7 2260.76  5301.9 2265.75
#Mann=4,-1,0
  4779.2   0.035       0  4804.3    0.07       0  4910.6    0.07       0
  4914.6    0.07       0
Bank Sta=4910.6,4914.6
Exp/Cntr=0.3,0.1

Type RM Length L Ch R = 1,8474,496,496,496
BEGIN DESCRIPTION:
Sweetwater Creek Trib 13 16.0
END DESCRIPTION:
XS GIS Cut Line= 3
      1369705.02      6825987.99      1369911.04      6825935.49
      1370104.97      6825688.03
#Sta/Elev= 30
  4787.4 2261.70  4805.2 2260.41  4813.9 2260.61  4818.3 2260.19  4846.1 2253.71
  4880.3 2249.92  4909.0 2245.61  4933.1 2240.94  4942.2 2241.54  4952.5 2240.92
  4968.8 2241.97  4973.9 2240.53  4993.8 2240.34  5013.2 2239.24  5013.4 2238.74
  5016.9 2238.74  5017.2 2239.24  5029.7 2241.73  5044.1 2240.94  5050.5 2242.05
  5085.7 2245.14  5149.9 2245.19  5186.9 2246.00  5236.7 2248.36  5257.5 2251.17
  5271.9 2254.13  5278.3 2256.53  5286.4 2257.44  5292.8 2259.53  5314.4 2262.09
#Mann=5,-1,0
  4787.4    0.07       0  4813.9   0.035       0  4909.0    0.07       0
  5013.2    0.07       0  5017.2    0.07       0
Bank Sta=5013.2,5017.2
Exp/Cntr=0.3,0.1

Type RM Length L Ch R = 1,7978,499,499,499
BEGIN DESCRIPTION:
Sweetwater Creek Trib 13 15.0
END DESCRIPTION:
XS GIS Cut Line= 3
      1370304.98      6826487.96      1370207.26      6826243.90
      1370205.00      6825988.01
#Sta/Elev= 30
  4737.1 2254.88  4739.7 2254.88  4746.5 2252.91  4751.9 2252.84  4758.6 2248.91
  4776.1 2244.78  4812.5 2240.64  4844.8 2239.17  4883.7 2239.22  4898.6 2238.69
  4908.0 2239.39  4913.4 2238.71  4920.2 2239.16  4937.6 2238.53  5000.0 2239.60
  5005.9 2239.11  5013.7 2237.20  5014.0 2236.70  5017.7 2236.70  5018.0 2237.20
  5025.9 2237.58  5035.9 2239.34  5085.9 2241.12  5095.9 2242.56  5105.9 2242.75
  5135.9 2245.06  5145.9 2246.73  5165.9 2247.46  5195.9 2249.52  5255.9 2255.70
#Mann=3,-1,0
  4737.1    0.07       0  5013.7    0.07       0  5018.0    0.07       0
Bank Sta=5013.7,5018
Exp/Cntr=0.3,0.1

Type RM Length L Ch R = 1,7479,499,499,499
BEGIN DESCRIPTION:
Sweetwater Creek Trib 13 14.0
END DESCRIPTION:
XS GIS Cut Line= 3
      1370355.03      6826487.98      1370614.92      6826326.45
      1370755.02      6826037.97
#Sta/Elev= 30
  4694.0 2254.27  4701.6 2253.09  4738.2 2251.43  4744.1 2249.74  4765.4 2248.05
  4817.3 2247.51  4911.8 2243.66  4917.7 2242.78  4933.0 2243.28  4941.2 2242.46
  4948.4 2239.37  4954.3 2239.49  4963.8 2236.39  4985.0 2235.24  5020.5 2236.78
  5042.7 2236.18  5052.9 2235.55  5062.8 2233.17  5063.1 2232.67  5067.1 2233.17
  5087.2 2235.84  5126.1 2237.05  5187.3 2236.82  5209.5 2238.43  5231.7 2237.96
  5246.4 2239.02  5276.2 2241.44  5306.6 2248.44  5317.9 2252.64  5320.7 2252.64
#Mann=4,-1,0
  4694.0    0.07       0  5062.8    0.07       0  5067.1    0.07       0
  5246.4   0.035       0
Bank Sta=5062.8,5067.1
Exp/Cntr=0.3,0.1

Type RM Length L Ch R = 1,6980,484,484,484
BEGIN DESCRIPTION:
Sweetwater Creek Trib 13 13.0
END DESCRIPTION:
XS GIS Cut Line= 3
      1370404.99      6826738.01      1370687.43      6826621.32
      1370855.01      6826638.00
#Sta/Elev= 30
  4694.4 2253.63  4709.1 2252.28  4726.9 2247.94  4738.4 2246.69  4770.2 2241.20
  4791.8 2235.68  4810.1 2234.02  4868.8 2233.85  4887.3 2239.55  4892.7 2240.23
  4910.8 2238.23  4916.6 2233.11  4932.4 2231.36  4954.1 2233.35  5000.0 2232.80
  5019.8 2232.19  5027.7 2229.90  5035.6 2229.32  5035.9 2228.82  5040.0 2229.32
  5047.8 2232.20  5088.0 2232.41  5098.0 2233.32  5108.1 2235.63  5115.5 2239.32
  5120.5 2240.28  5128.2 2244.36  5148.3 2252.86  5158.3 2255.48  5168.4 2256.66
#Mann=3,-1,0
  4694.4    0.07       0  5035.6    0.07       0  5040.0    0.07       0
Bank Sta=5035.6,5040
Exp/Cntr=0.3,0.1

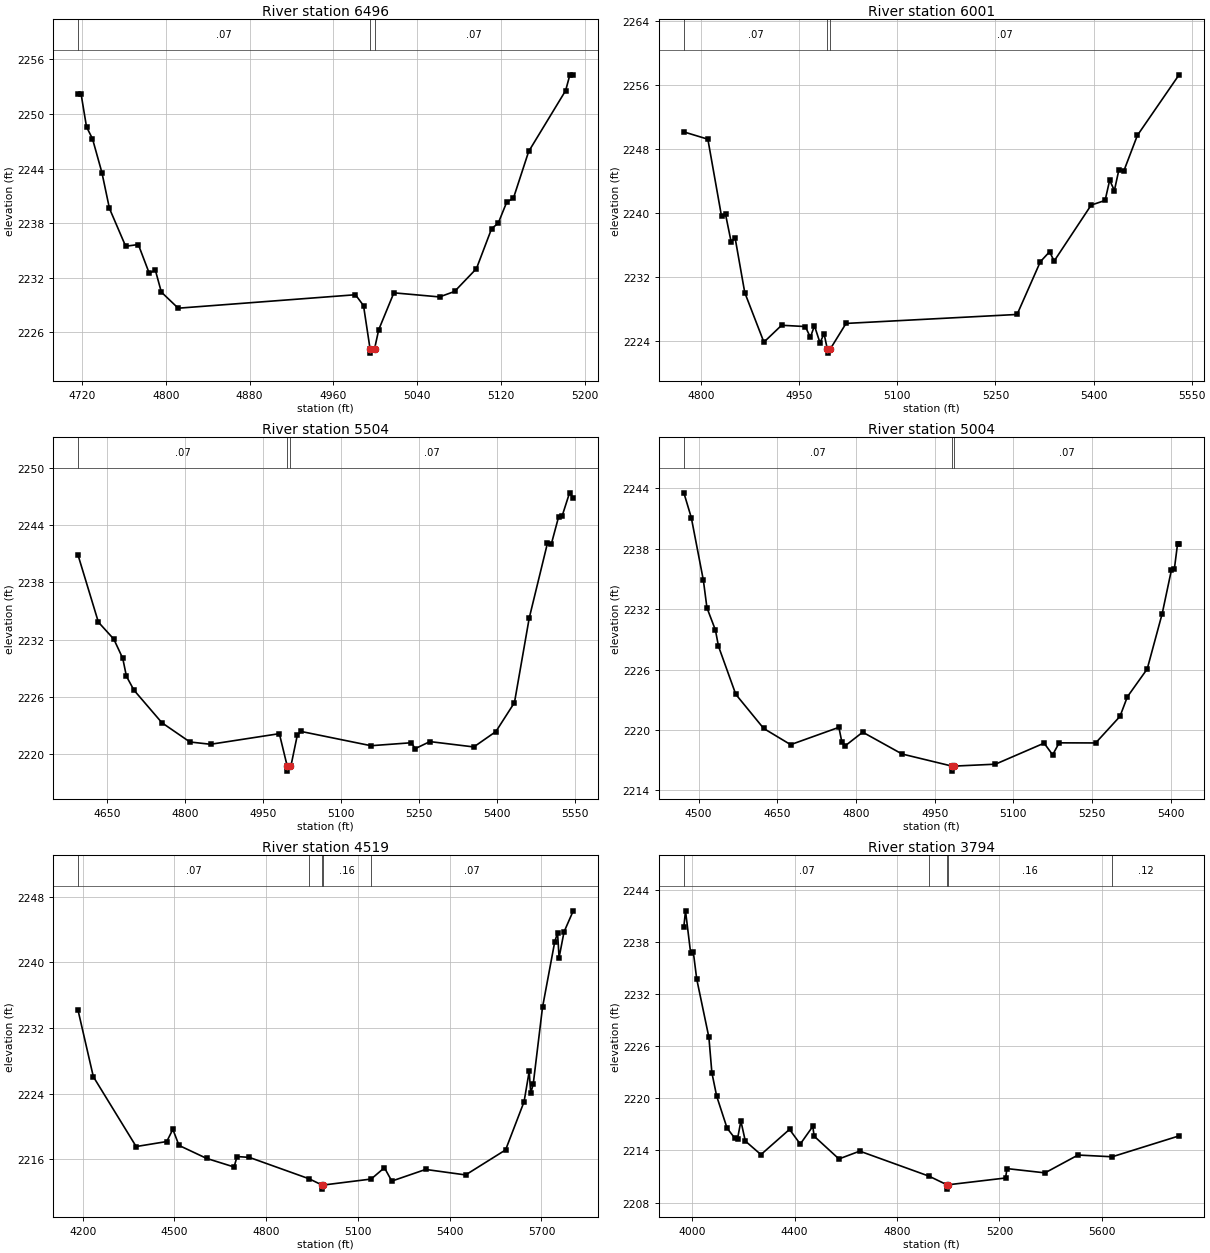
Type RM Length L Ch R = 1,6496,495,495,495
BEGIN DESCRIPTION:
Sweetwater Creek Trib 13 12.0
END DESCRIPTION:
XS GIS Cut Line= 3
      1370604.97      6827188.02      1370854.86      6827053.06
      1371005.03      6826937.98
#Sta/Elev= 30
  4716.0 2252.20  4718.9 2252.20  4724.1 2248.58  4729.8 2247.28  4738.8 2243.56
  4746.0 2239.62  4761.5 2235.46  4773.6 2235.65  4784.1 2232.47  4789.8 2232.86
  4795.6 2230.42  4811.7 2228.65  4981.1 2230.13  4988.8 2228.93  4995.0 2224.21
  4995.3 2223.71  4999.4 2224.21  5003.3 2226.28  5017.8 2230.34  5061.4 2229.89
  5075.8 2230.49  5096.7 2233.00  5111.2 2237.40  5117.5 2237.99  5125.7 2240.33
  5132.0 2240.73  5146.6 2245.88  5181.9 2252.57  5186.0 2254.31  5189.2 2254.31
#Mann=3,-1,0
  4716.0    0.07       0  4995.0    0.07       0  4999.4    0.07       0
Bank Sta=4995,4999.4
Exp/Cntr=0.3,0.1

Type RM Length L Ch R = 1,6001,497,497,497
BEGIN DESCRIPTION:
Sweetwater Creek Trib 13 11.0
END DESCRIPTION:
XS GIS Cut Line= 3
      1370704.99      6827337.99      1370887.98      6827471.48
      1371254.99      6827088.01
#Sta/Elev= 30
  4773.5 2250.17  4810.2 2249.26  4831.1 2239.63  4837.2 2239.89  4845.7 2236.48
  4851.9 2236.92  4866.6 2230.11  4895.9 2223.91  4923.0 2226.02  4959.2 2225.86
  4967.0 2224.52  4973.2 2225.96  4981.7 2223.83  4987.9 2224.97  4992.9 2223.04
  4993.2 2222.54  4997.3 2223.04  5021.5 2226.25  5283.1 2227.37  5318.7 2233.96
  5332.8 2235.20  5339.8 2234.04  5396.4 2241.03  5417.7 2241.61  5424.7 2244.14
  5431.9 2242.85  5438.8 2245.44  5446.1 2245.24  5467.1 2249.74  5530.8 2257.30
#Mann=3,-1,0
  4773.5    0.07       0  4992.9    0.07       0  4997.3    0.07       0
Bank Sta=4992.9,4997.3
Exp/Cntr=0.3,0.1

Type RM Length L Ch R = 1,5504,500,500,500
BEGIN DESCRIPTION:
Sweetwater Creek Trib 13 10.0
END DESCRIPTION:
XS GIS Cut Line= 3
      1370905.02      6828287.96      1371054.93      6827910.76
      1371454.99      6827538.01
#Sta/Elev= 30
  4594.1 2240.84  4633.2 2233.83  4662.9 2232.05  4680.1 2230.04  4687.2 2228.16
  4701.7 2226.71  4755.5 2223.30  4809.3 2221.29  4849.1 2221.05  4981.4 2222.16
  4996.6 2218.74  4996.9 2218.24  5001.0 2218.74  5003.5 2218.74  5016.0 2222.02
  5023.3 2222.39  5157.7 2220.90  5235.4 2221.21  5242.7 2220.59  5271.0 2221.33
  5355.5 2220.77  5398.0 2222.38  5433.7 2225.41  5462.1 2234.25  5497.2 2242.09
  5504.6 2241.99  5518.7 2244.86  5525.6 2244.96  5539.7 2247.36  5546.8 2246.85
#Mann=3,-1,0
  4594.1    0.07       0  4996.6    0.07       0  5001.0    0.07       0
Bank Sta=4996.6,5001
Exp/Cntr=0.3,0.1

Type RM Length L Ch R = 1,5004,485,485,485
BEGIN DESCRIPTION:
Sweetwater Creek Trib 13 9.0
END DESCRIPTION:
XS GIS Cut Line= 3
      1370955.04      6828337.98      1371435.12      6828117.72
      1371605.01      6827737.99
#Sta/Elev= 30
  4471.8 2243.56  4486.0 2241.09  4509.0 2234.87  4515.8 2232.14  4532.0 2229.92
  4537.8 2228.32  4570.8 2223.54  4624.0 2220.15  4675.4 2218.54  4767.4 2220.26
  4772.9 2218.84  4779.8 2218.44  4812.8 2219.78  4887.9 2217.61  4983.0 2216.41
  4983.4 2215.91  4987.6 2216.41  5065.9 2216.60  5158.7 2218.69  5175.0 2217.53
  5187.4 2218.72  5257.0 2218.71  5303.4 2221.35  5317.4 2223.29  5355.3 2226.06
  5383.9 2231.57  5401.6 2235.93  5407.1 2236.01  5413.2 2238.51  5416.0 2238.51
#Mann=3,-1,0
  4471.8    0.07       0  4983.0    0.07       0  4987.6    0.07       0
Bank Sta=4983,4987.6
Exp/Cntr=0.3,0.1

Type RM Length L Ch R = 1,4519,725,725,725
BEGIN DESCRIPTION:
Sweetwater Creek Trib 13 8.1
END DESCRIPTION:
XS GIS Cut Line= 3
      1371005.03      6828388.00      1371820.23      6828387.47
      1371904.99      6827588.05
#Sta/Elev= 30
  4184.8 2234.17  4234.8 2226.07  4374.8 2217.56  4474.8 2218.17  4494.8 2219.66
  4514.8 2217.70  4604.8 2216.12  4694.8 2215.07  4704.8 2216.34  4744.8 2216.24
  4940.3 2213.63  4982.5 2212.87  4982.8 2212.37  4987.1 2212.87  5143.2 2213.60
  5186.5 2214.98  5210.6 2213.35  5321.3 2214.77  5452.0 2214.10  5582.7 2217.15
  5643.1 2223.02  5659.9 2226.73  5664.9 2224.04  5673.2 2225.21  5703.4 2234.52
  5743.6 2242.55  5752.6 2243.60  5757.6 2240.58  5773.8 2243.72  5803.9 2246.29
#Mann=5,-1,0
  4184.8    0.07       0  4940.3    0.16       0  4982.5    0.07       0
  4987.1    0.16       0  5143.2    0.07       0
Bank Sta=4982.5,4987.1
Exp/Cntr=0.3,0.1

Type RM Length L Ch R = 1,3794,432,432,432
BEGIN DESCRIPTION:
Sweetwater Creek Trib 13 4378
END DESCRIPTION:
XS GIS Cut Line= 4
      1370888.74      6828694.58      1371905.19      6828874.19
      1372227.25      6828329.99      1372227.25      6828061.04
#Sta/Elev= 30
  3967.8 2239.73  3974.2 2241.55  3994.5 2236.65  4004.6 2236.83  4018.0 2233.71
  4065.6 2226.99  4077.2 2222.93  4096.0 2220.23  4136.6 2216.56  4167.1 2215.39
  4177.3 2215.34  4190.5 2217.38  4207.7 2215.08  4268.7 2213.52  4380.4 2216.42
  4422.3 2214.73  4471.3 2216.77  4476.4 2215.64  4573.3 2213.02  4654.5 2213.92
  4925.1 2211.04  4995.0 2210.05  4995.3 2209.55  4999.8 2210.05  5223.8 2210.83
  5229.6 2211.91  5377.9 2211.42  5506.8 2213.47  5640.2 2213.27  5901.3 2215.67
#Mann=5,-1,0
  3967.8    0.07       0  4925.1    0.16       0  4995.0    0.07       0
  4999.8    0.16       0  5640.2    0.12       0
Bank Sta=4995,4999.8
Exp/Cntr=0.3,0.1

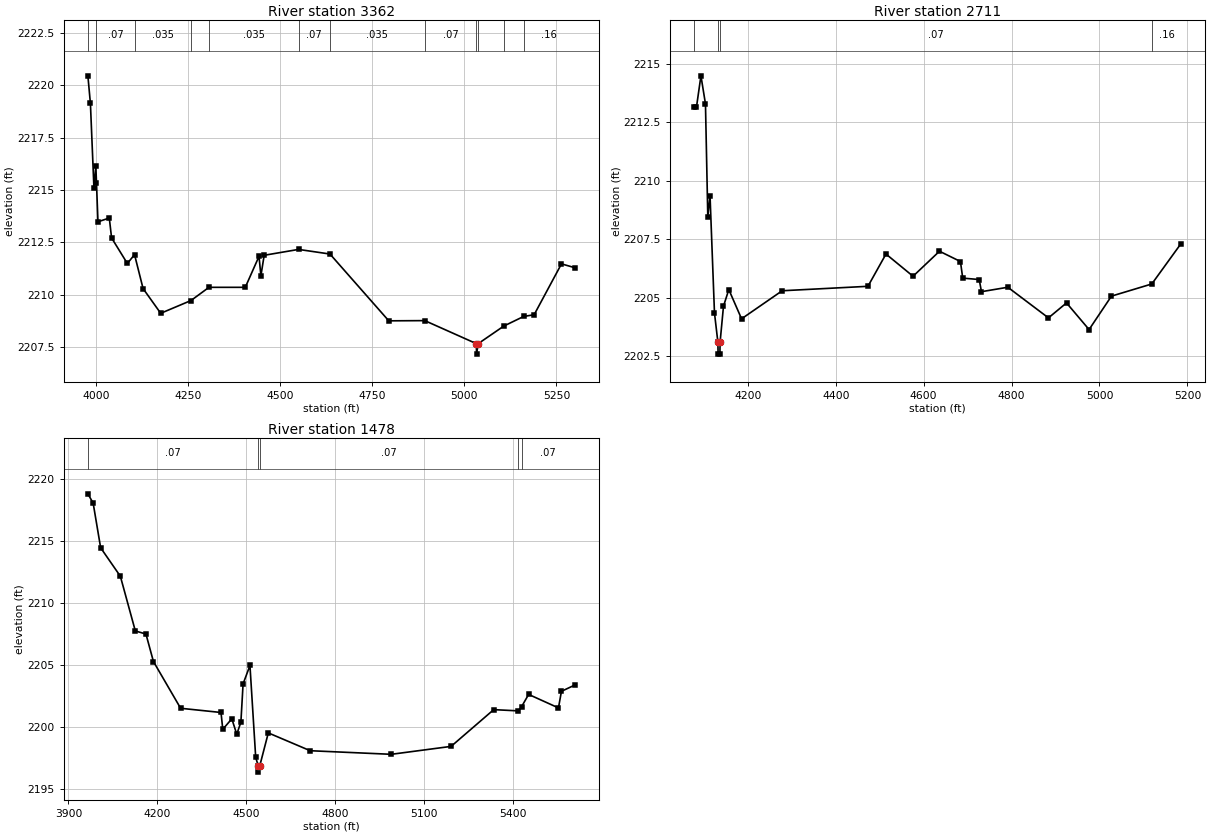
Type RM Length L Ch R = 1,3362,651,651,651
BEGIN DESCRIPTION:
Sweetwater Creek Trib 13 4377
END DESCRIPTION:
XS GIS Cut Line= 3
      1370878.25      6829038.32      1371875.24      6829267.99
      1372133.47      6829116.47
#Sta/Elev= 30
  3976.9 2220.45  3983.8 2219.13  3993.4 2215.08  3998.5 2216.16  4000.3 2215.33
  4004.3 2213.48  4035.1 2213.66  4041.3 2212.71  4084.1 2211.49  4103.7 2211.91
  4126.9 2210.29  4174.8 2209.11  4257.1 2209.72  4305.9 2210.35  4404.6 2210.35
  4441.9 2211.83  4447.0 2210.90  4455.9 2211.88  4549.3 2212.16  4634.7 2211.94
  4794.5 2208.75  4892.3 2208.76  5032.5 2207.66  5032.9 2207.16  5037.4 2207.66
  5107.0 2208.50  5161.1 2208.96  5189.4 2209.04  5263.7 2211.47  5299.4 2211.29
#Mann=12,-1,0
  3976.9   0.035       0  4000.3    0.07       0  4103.7   0.035       0
  4257.1    0.07       0  4305.9   0.035       0  4549.3    0.07       0
  4634.7   0.035       0  4892.3    0.07       0  5032.5    0.07       0
  5037.4    0.07       0  5107.0    0.07       0  5161.1    0.16       0
Bank Sta=5032.5,5037.4
Exp/Cntr=0.3,0.1

Type RM Length L Ch R = 1,2711,1233,1233,1233
BEGIN DESCRIPTION:
Sweetwater Creek Trib 13 4376
END DESCRIPTION:
XS GIS Cut Line= 3
      1370930.37      6829606.03      1371828.07      6829814.56
      1372011.90      6829840.16
#Sta/Elev= 30
  4078.4 2213.16  4083.3 2213.16  4093.4 2214.49  4103.7 2213.29  4109.0 2208.46
  4114.1 2209.36  4124.2 2204.35  4132.0 2203.09  4132.4 2202.59  4136.6 2202.59
  4136.9 2203.09  4144.7 2204.64  4156.8 2205.35  4185.8 2204.10  4278.2 2205.30
  4473.3 2205.49  4514.3 2206.87  4575.9 2205.92  4636.0 2206.99  4683.7 2206.55
  4688.9 2205.84  4726.4 2205.78  4731.5 2205.26  4791.5 2205.45  4883.9 2204.14
  4925.0 2204.78  4976.3 2203.64  5027.2 2205.07  5119.0 2205.59  5185.6 2207.32
#Mann=4,-1,0
  4078.4    0.07       0  4132.0    0.07       0  4136.9    0.07       0
  5119.0    0.16       0
Bank Sta=4132,4136.9
Exp/Cntr=0.3,0.1

Type RM Length L Ch R = 1,1478,0,0,0
BEGIN DESCRIPTION:
Sweetwater Creek Trib 13 4375
END DESCRIPTION:
XS GIS Cut Line= 3
      1370532.80      6830507.07      1371504.62      6830860.81
      1372109.20      6830791.80
#Sta/Elev= 30
  3965.8 2218.83  3983.6 2218.08  4008.9 2214.47  4075.4 2212.17  4125.9 2207.75
  4161.8 2207.50  4187.0 2205.28  4278.8 2201.50  4415.1 2201.16  4421.1 2199.80
  4451.6 2200.65  4468.3 2199.40  4482.2 2200.38  4489.6 2203.47  4512.8 2204.96
  4532.2 2197.53  4540.9 2196.84  4541.3 2196.34  4545.8 2196.84  4574.7 2199.51
  4716.2 2198.07  4989.8 2197.78  5191.6 2198.42  5335.5 2201.39  5418.3 2201.29
  5429.6 2201.63  5453.3 2202.62  5554.0 2201.53  5564.0 2202.87  5608.5 2203.37
#Mann=5,-1,0
  3965.8    0.07       0  4540.9    0.07       0  4545.8    0.07       0
  5418.3    0.16       0  5429.6    0.07       0
Bank Sta=4540.9,4545.8
Exp/Cntr=0.3,0.1

Chan Stop Cuts=-1