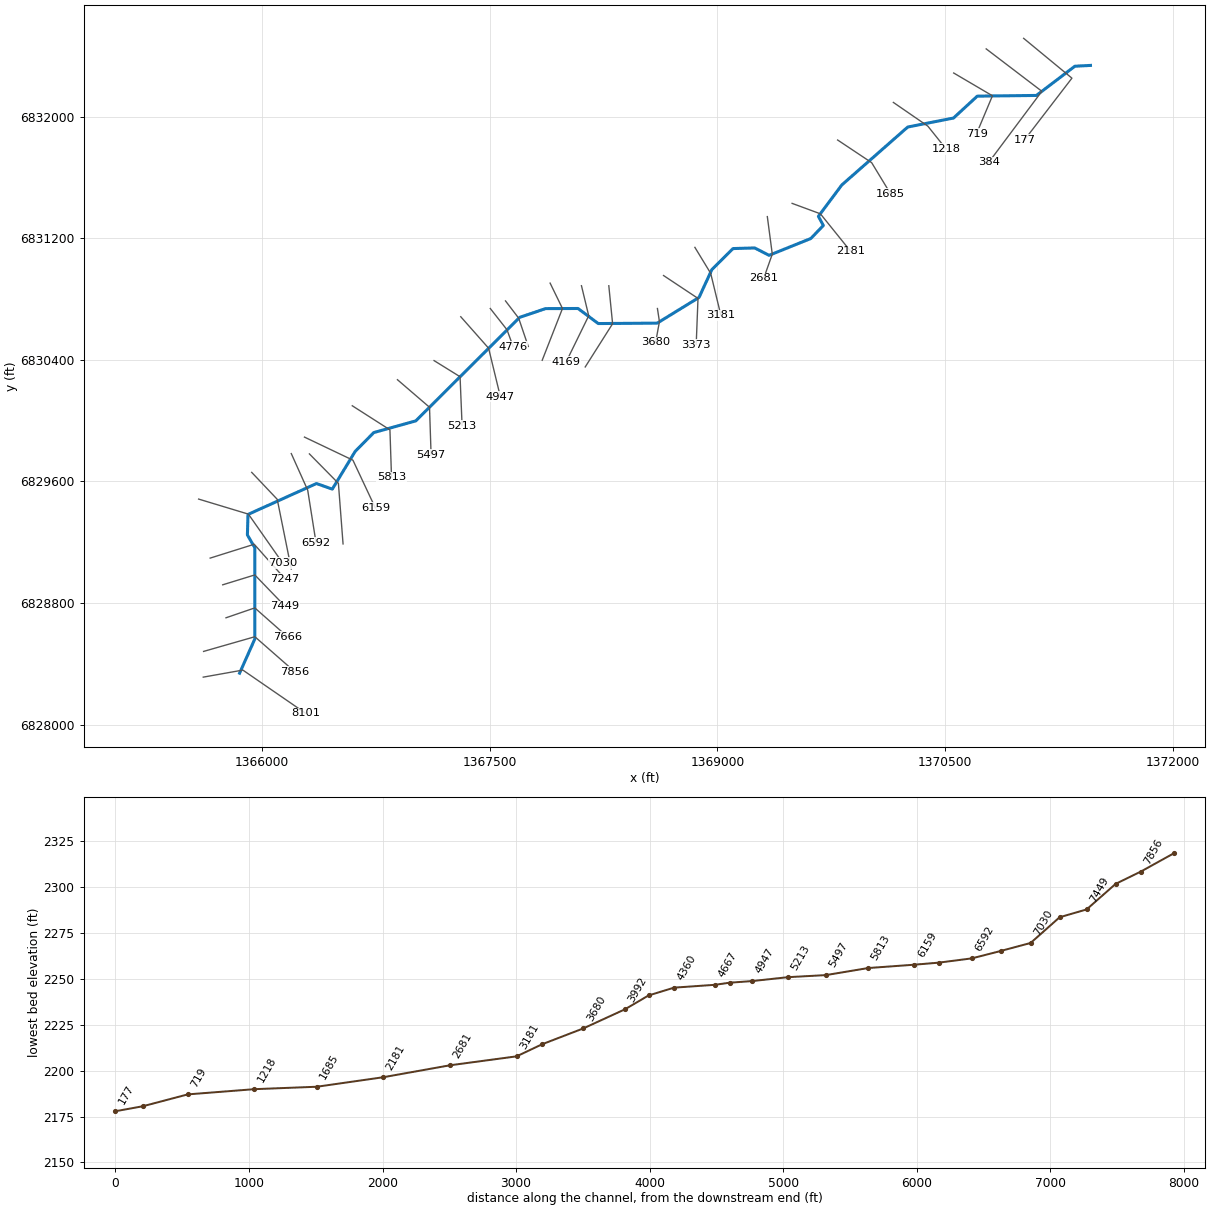
--- Sweetwater Creek Trib 14.prj (project) ---

Proj Title=Sweetwater Creek Trib 14 Base Level Engineering
Current Plan=p01
Default Exp/Contr=0.3,0.1
English Units
Geom File=g01
Flow File=f01
Plan File=p01
Y Axis Title=Elevation
X Axis Title(PF)=Main Channel Distance
X Axis Title(XS)=Station
BEGIN DESCRIPTION:
Sweetwater Creek Trib 14
END DESCRIPTION:
DSS Export Rating Curves= 0
DSS Export Rating Curve Sorted= 0
DSS Export Volume Flow Curves= 0
DXF OffsetX= 0
DXF OffsetY= 0
DXF ScaleX= 1
DXF ScaleY= 10

--- Sweetwater Creek Trib 14.p01 (plan) ---

Plan Title=Multiple Run
Short Identifier=Multiple
Geom File=g01
Flow File=f01
Subcritical Flow
K Sum by GR= 0
Std Step Tol= 0.01
Critical Tol= 0.01
Num of Std Step Trials= 20
Max Error Tol= 0.3
Flow Tol Ratio= 0.001
Split Flow NTrial= 30
Split Flow Tol= 0.02
Split Flow Ratio= 0.02
Log Output Level= 0
Friction Slope Method= 1
Unsteady Friction Slope Method= 2
Unsteady Bridges Friction Slope Method= 1
Parabolic Critical Depth
Global Vel Dist=  1 , 1 , 1
Global Log Level= 0
CheckData=True
Encroach Param= -1, 0, 0, 0
BEGIN DESCRIPTION:
Multiple Run
END DESCRIPTION:

--- Sweetwater Creek Trib 14.f01 (steady flow) ---

Flow Title=Multiple
Number of Profiles=7
Profile Names=10-year,25-year,50-year,1pct_min,100-year,1pct_plu,500-year
River Rch & RM= Sweetwater Creek,Reach-1,8101
     264     376     471     294     587    1171     921
Boundary for River Rch & Prof#=Sweetwater Creek,Reach-1,1
Up Type=0
Dn Type=3
Dn Slope=0.005
Boundary for River Rch & Prof#=Sweetwater Creek,Reach-1,2
Up Type=0
Dn Type=3
Dn Slope=0.005
Boundary for River Rch & Prof#=Sweetwater Creek,Reach-1,3
Up Type=0
Dn Type=3
Dn Slope=0.005
Boundary for River Rch & Prof#=Sweetwater Creek,Reach-1,4
Up Type=0
Dn Type=3
Dn Slope=0.005
Boundary for River Rch & Prof#=Sweetwater Creek,Reach-1,5
Up Type=0
Dn Type=3
Dn Slope=0.005
Boundary for River Rch & Prof#=Sweetwater Creek,Reach-1,6
Up Type=0
Dn Type=3
Dn Slope=0.005
Boundary for River Rch & Prof#=Sweetwater Creek,Reach-1,7
Up Type=0
Dn Type=3
Dn Slope=0.005

--- Sweetwater Creek Trib 14.g01 (geometry) ---

Geom Title=Existing Conditions
Program Version=4.10

River Reach=Sweetwater Creek,Reach-1
Reach XY= 30
        1365855.        6828338.       1365955.2      6828562.92
       1365955.2      6829163.08      1365906.36      6829247.68
      1365910.16      6829382.59      1366361.13      6829586.16
      1366465.08       6829549.1      1366615.76      6829797.68
      1366738.25      6829921.54      1367014.79      6829998.52
      1367698.83      6830680.14      1367868.92      6830737.32
      1368082.34      6830738.16       1368215.4      6830638.96
      1368603.45      6830641.75      1368878.84      6830810.86
      1368963.14      6830994.06      1369102.55      6831132.55
      1369245.34      6831136.61      1369339.61      6831088.09
      1369614.73      6831198.76        1369697.      6831284.65
       1369664.3      6831344.67      1369818.62      6831551.24
      1370252.55      6831932.53       1370553.5      6831991.61
      1370710.44      6832135.83      1371099.48      6832140.35
       1371352.5      6832332.65        1371455.        6832338.

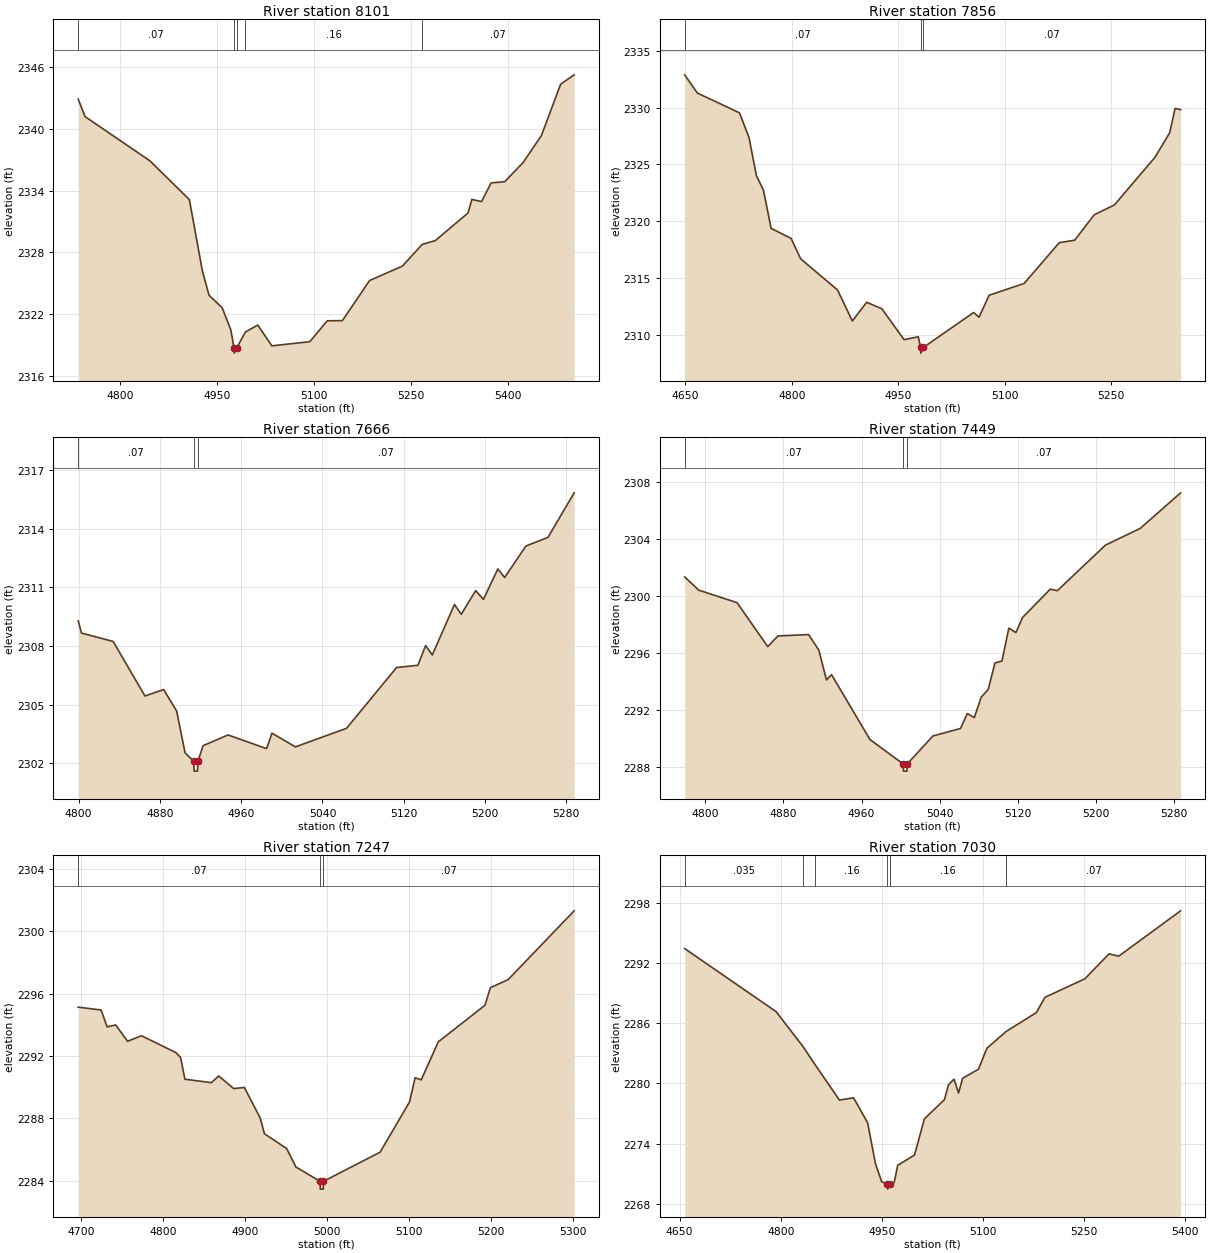
Type RM Length L Ch R = 1 ,8101    ,245,245,245
BEGIN DESCRIPTION:
Sweetwater Creek Trib 14 4238
END DESCRIPTION:
XS GIS Cut Line= 3
      1365615.69      6828311.84      1365876.37      6828358.33
      1366290.35      6828073.33
#Sta/Elev= 30
  4735.2  2342.9  4745.8  2341.2  4846.2  2336.9  4907.2 2333.13  4927.5 2326.15
  4937.7 2323.83    4958 2322.62  4971.4 2320.46  4976.3 2318.71  4976.5 2318.21
  4980.3 2318.71    4994 2320.26    5013 2320.94  5034.8 2318.92  5093.5 2319.32
  5120.5 2321.35    5144 2321.37  5186.1 2325.27  5236.9 2326.67  5267.5 2328.78
  5287.6 2329.14  5338.3 2331.83  5344.4 2333.15  5359.3 2332.94  5374.2 2334.76
  5395.1 2334.87  5423.3 2336.71  5451.9 2339.35  5481.7 2344.35  5502.6 2345.26
#Mann= 5 ,-1 , 0
  4735.2     .07       0  4976.3     .07       0  4980.3     .07       0
    4994     .16       0  5267.5     .07       0
Bank Sta=4976.3,4980.3
XS Rating Curve= 0 ,0
Exp/Cntr=0.3,0.1

Type RM Length L Ch R = 1 ,7856    ,190,190,190
BEGIN DESCRIPTION:
Sweetwater Creek Trib 14 4237
END DESCRIPTION:
XS GIS Cut Line= 3
      1365617.93      6828481.13      1365955.45      6828577.81
      1366216.88      6828348.72
#Sta/Elev= 30
  4648.9 2332.88  4666.7 2331.28  4726.1 2329.53  4739.5 2327.37  4749.9 2324.01
  4759.9 2322.71  4770.7 2319.35  4798.8 2318.47  4812.3 2316.67  4864.3 2313.92
  4885.1 2311.19  4905.3 2312.84  4926.7 2312.27  4957.9 2309.55    4978  2309.8
  4981.2 2308.86  4981.5 2308.36  4985.2 2308.86    5056 2311.94  5063.6 2311.52
  5077.8 2313.46  5127.2  2314.5  5176.6 2318.09  5198.4 2318.31  5225.9 2320.55
  5254.4 2321.42  5311.3  2325.6  5332.2 2327.77  5339.8 2329.92  5347.6 2329.81
#Mann= 3 ,-1 , 0
  4648.9     .07       0  4981.2     .07       0  4985.2     .07       0
Bank Sta=4981.2,4985.2
XS Rating Curve= 0 ,0
Exp/Cntr=0.3,0.1

Type RM Length L Ch R = 1 ,7666    ,217,217,217
BEGIN DESCRIPTION:
Sweetwater Creek Trib 14 4236
END DESCRIPTION:
XS GIS Cut Line= 3
      1365765.49      6828702.48      1365955.02      6828767.58
      1366170.67      6828577.14
#Sta/Elev= 30
  4799.6 2309.28  4802.8 2308.66    4834 2308.23  4865.3 2305.44  4883.7 2305.77
  4896.5 2304.67  4904.8 2302.53  4913.4  2302.1  4913.6  2301.6  4917.1  2301.6
  4917.4  2302.1  4922.5  2302.9  4947.1 2303.45    4985 2302.75  4990.3 2303.54
  5013.4 2302.84  5063.7 2303.79    5113  2306.9  5133.9 2307.01  5141.5 2308.02
  5148.1 2307.54  5169.9 2310.12  5176.6 2309.62  5190.8 2310.83  5198.4 2310.38
  5212.6 2311.94  5219.3  2311.5  5240.2 2313.11  5261.9 2313.55  5287.7 2315.83
#Mann= 3 ,-1 , 0
  4799.6     .07       0  4913.4     .07       0  4917.4     .07       0
Bank Sta=4913.4,4917.4
XS Rating Curve= 0 ,0
Exp/Cntr=0.3,0.1

Type RM Length L Ch R = 1 ,7449    ,202,202,202
BEGIN DESCRIPTION:
Sweetwater Creek Trib 14 4234
END DESCRIPTION:
XS GIS Cut Line= 3
      1365743.81       6828919.5      1365955.01      6828984.59
      1366153.94      6828778.41
#Sta/Elev= 30
    4779 2301.36  4793.4 2300.43  4832.6 2299.55    4864 2296.46  4874.4 2297.21
  4905.8 2297.31  4916.3 2296.21  4924.1 2294.12  4929.3 2294.49  4968.6 2289.93
  5002.7 2288.21  5002.9 2287.71  5006.4 2287.71  5006.7 2288.21    5033 2290.18
  5061.3 2290.71  5068.2 2291.76  5075.4 2291.47  5082.4  2292.9  5089.6 2293.45
  5096.5 2295.31  5103.7 2295.45  5110.7 2297.76  5117.9 2297.45  5124.8 2298.51
  5153.1  2300.5  5160.3 2300.39  5209.7  2303.6  5245.2 2304.77  5286.5 2307.27
#Mann= 3 ,-1 , 0
    4779     .07       0  5002.7     .07       0  5006.7     .07       0
Bank Sta=5002.7,5006.7
XS Rating Curve= 0 ,0
Exp/Cntr=0.3,0.1

Type RM Length L Ch R = 1 ,7247    ,217,217,217
BEGIN DESCRIPTION:
Sweetwater Creek Trib 14 4233
END DESCRIPTION:
XS GIS Cut Line= 3
      1365661.31      6829095.27      1365951.22      6829186.43
      1366151.73      6828960.74
#Sta/Elev= 30
  4696.1 2295.13    4724 2294.95  4731.4 2293.87  4741.9 2293.99  4756.4 2292.94
  4773.3  2293.3  4815.3 2292.22  4821.2  2291.9  4826.4 2290.51  4858.8 2290.29
  4867.7 2290.72    4886 2289.91  4899.1 2289.98  4918.4 2288.02  4923.6 2287.01
  4950.8 2286.06    4962 2284.88  4991.6 2283.96  4991.9 2283.46  4995.4 2283.46
  4995.6 2283.96  5064.9 2285.83  5100.9 2289.06  5107.6  2290.6  5115.1 2290.47
    5136 2292.91  5192.9 2295.25  5199.6 2296.38  5221.3  2296.9  5301.9 2301.31
#Mann= 3 ,-1 , 0
  4696.1     .07       0  4991.6     .07       0  4995.6     .07       0
Bank Sta=4991.6,4995.6
XS Rating Curve= 0 ,0
Exp/Cntr=0.3,0.1

Type RM Length L Ch R = 1 ,7030    ,220,220,220
BEGIN DESCRIPTION:
Sweetwater Creek Trib 14 4241
END DESCRIPTION:
XS GIS Cut Line= 3
      1365585.33      6829483.73      1365913.08      6829384.65
      1366138.65      6829062.83
#Sta/Elev= 30
  4657.6 2293.44  4793.1 2287.16  4832.8  2283.7  4851.5 2281.82  4887.1 2278.34
    4908 2278.57  4928.9 2276.08  4940.6 2271.98  4949.8  2270.2  4958.2 2269.97
  4958.5 2269.47  4962.2 2269.97  4968.3 2270.14  4973.5 2271.84  4998.4 2272.87
  5013.1 2276.47  5042.8 2278.39  5048.9 2279.88    5057 2280.43  5063.7 2279.05
  5069.8 2280.52  5093.3 2281.42  5105.8 2283.51  5134.5 2285.19  5179.1 2287.06
  5191.8 2288.58  5251.1 2290.43  5286.8 2292.91  5301.2 2292.68    5393  2297.2
#Mann= 6 ,-1 , 0
  4657.6    .035       0  4832.8     .07       0  4851.5     .16       0
  4958.2     .07       0  4962.2     .16       0  5134.5     .07       0
Bank Sta=4958.2,4962.2
XS Rating Curve= 0 ,0
Exp/Cntr=0.3,0.1

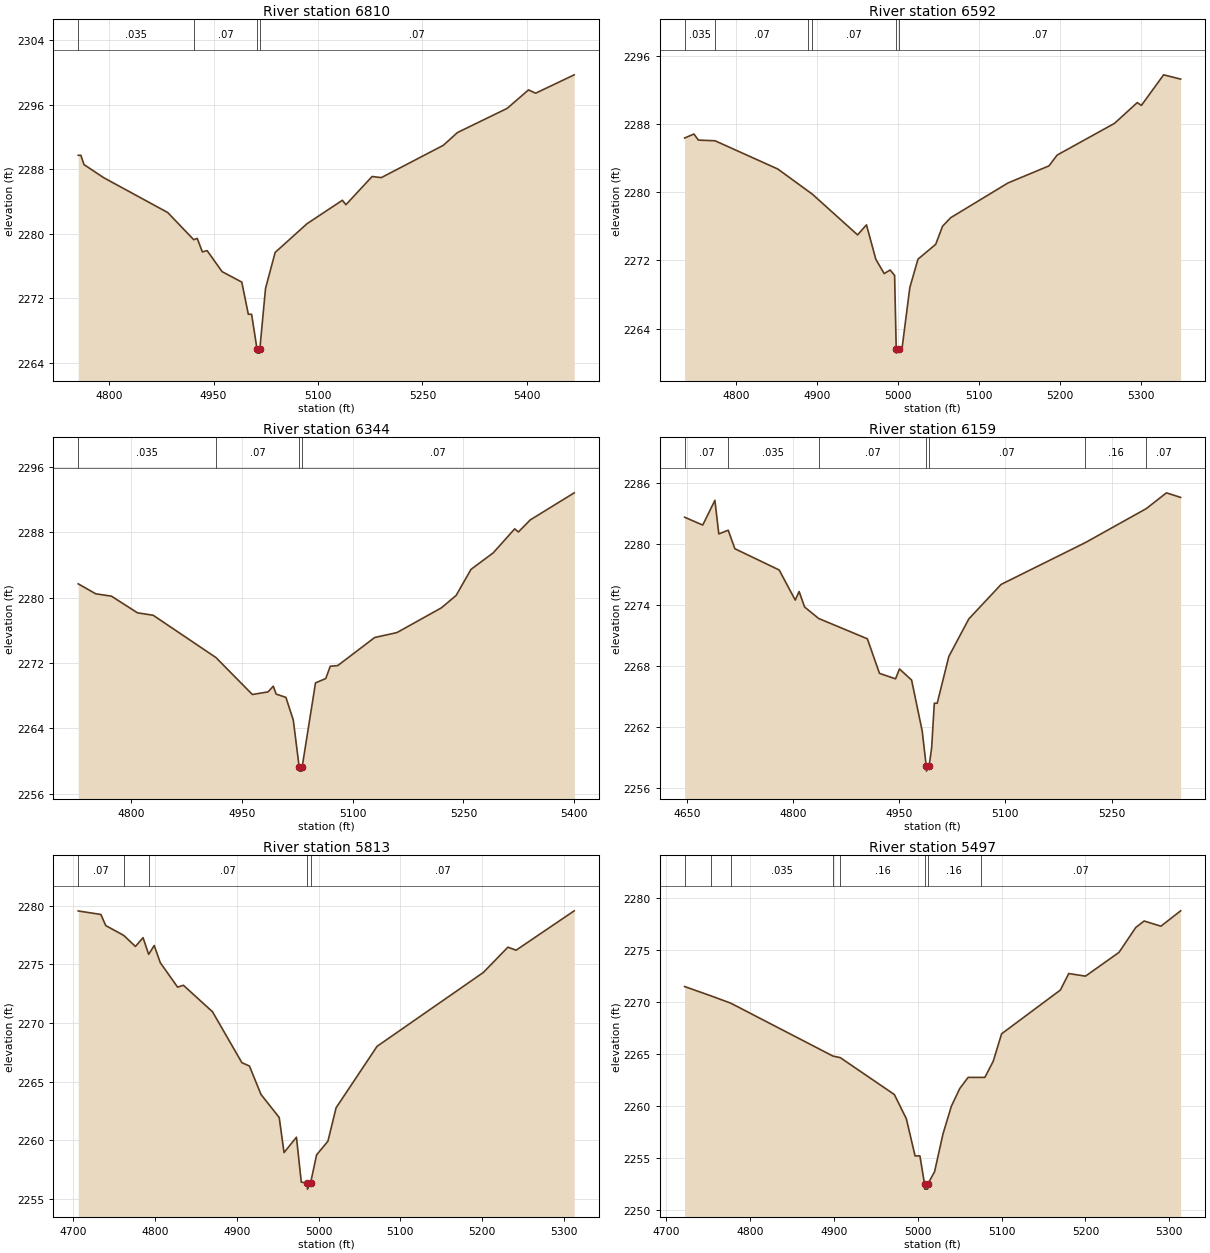
Type RM Length L Ch R = 1 ,6810    ,218,218,218
BEGIN DESCRIPTION:
Sweetwater Creek Trib 14 4232
END DESCRIPTION:
XS GIS Cut Line= 3
      1365934.73      6829659.51      1366102.68      6829482.23
      1366195.16      6829023.66
#Sta/Elev= 30
  4755.8 2289.73  4759.6 2289.73  4764.1 2288.58  4792.4 2286.95  4884.3 2282.63
  4921.6 2279.26  4926.7 2279.42    4934 2277.75  4940.9  2277.9  4962.3  2275.3
  4990.6    2274    5000 2270.01  5004.7 2270.01  5012.5 2265.69  5012.8 2265.19
  5016.3 2265.19  5016.5 2265.69  5024.7 2273.22  5038.5 2277.68  5084.2 2281.24
    5135 2284.15  5140.1  2283.6  5177.7  2287.1  5190.9 2286.96  5279.8 2290.96
  5300.2 2292.55  5371.6 2295.55  5402.2 2297.84  5412.4 2297.43  5467.8 2299.71
#Mann= 4 ,-1 , 0
  4755.8    .035       0  4921.6     .07       0  5012.5     .07       0
  5016.5     .07       0
Bank Sta=5012.5,5016.5
XS Rating Curve= 0 ,0
Exp/Cntr=0.3,0.1

Type RM Length L Ch R = 1 ,6592    ,248,248,248
BEGIN DESCRIPTION:
Sweetwater Creek Trib 14 4230
END DESCRIPTION:
XS GIS Cut Line= 3
      1366195.17      6829783.18      1366303.28      6829542.22
      1366357.92      6829197.22
#Sta/Elev= 30
  4735.9 2286.36  4747.4 2286.83  4752.9 2286.12  4773.5 2286.04  4851.2 2282.72
  4889.1  2280.1  4893.9 2279.77  4949.8 2274.99  4960.8 2276.17  4972.4 2272.12
  4982.7 2270.45  4990.1 2270.87  4995.6 2270.23  4997.6 2261.61  4997.8 2261.11
  5001.6 2261.61  5004.7 2261.61  5014.4  2268.8  5024.5 2272.14  5046.4 2273.88
  5054.9 2276.01    5065 2277.01  5135.9 2281.09  5186.5 2283.09  5196.6 2284.36
  5267.5 2288.08  5295.7 2290.52  5300.8 2290.19  5328.3 2293.78  5349.3 2293.28
#Mann= 6 ,-1 , 0
  4735.9    .035       0  4773.5     .07       0  4889.1    .035       0
  4893.9     .07       0  4997.6     .07       0  5001.6     .07       0
Bank Sta=4997.6,5001.6
XS Rating Curve= 0 ,0
Exp/Cntr=0.3,0.1

Type RM Length L Ch R = 1 ,6344    ,185,185,185
BEGIN DESCRIPTION:
Sweetwater Creek Trib 14 4231
END DESCRIPTION:
XS GIS Cut Line= 3
      1366314.48      6829781.07      1366505.22      6829587.43
      1366535.87      6829188.61
#Sta/Elev= 30
  4728.2  2281.7  4751.9 2280.48  4773.2 2280.19  4808.5 2278.15  4829.8 2277.85
  4914.8 2272.67  4964.1 2268.15  4985.3 2268.47  4992.4 2269.17  4996.3  2268.2
  5009.5  2267.8  5019.5 2265.03  5027.5 2259.27  5027.8 2258.77  5031.3 2258.77
  5031.5 2259.27  5049.6 2269.57  5063.5 2270.11  5069.6 2271.61  5079.7 2271.69
  5129.8 2275.13  5159.9 2275.73  5220.1 2278.76  5240.1 2280.28  5260.2 2283.47
  5290.3 2285.49  5319.4 2288.43  5324.4 2288.05  5340.4 2289.52    5400 2292.84
#Mann= 4 ,-1 , 0
  4728.2    .035       0  4914.8     .07       0  5027.5     .07       0
  5031.5     .07       0
Bank Sta=5027.5,5031.5
XS Rating Curve= 0 ,0
Exp/Cntr=0.3,0.1

Type RM Length L Ch R = 1 ,6159    ,346,346,346
BEGIN DESCRIPTION:
Sweetwater Creek Trib 14 4229
END DESCRIPTION:
XS GIS Cut Line= 3
      1366281.98       6829891.7      1366600.81      6829739.74
      1366748.56       6829425.1
#Sta/Elev= 30
  4646.8 2282.62  4672.4 2281.85  4689.6 2284.28  4695.1 2280.98  4708.4 2281.34
  4717.8 2279.52  4780.4 2277.43  4803.1 2274.47  4808.6 2275.31  4816.3 2273.79
  4836.1 2272.66    4905 2270.66  4922.1 2267.26  4944.8 2266.72  4950.4 2267.69
  4967.5  2266.6  4982.5 2261.58  4988.2 2258.14  4988.5 2257.64  4992.2 2258.14
  4995.8 2259.92  4999.6 2264.32  5003.7 2264.32  5020.1 2268.92  5048.4 2272.62
    5094 2276.01  5213.2 2280.13  5299.2 2283.47  5327.6 2285.02  5347.6 2284.57
#Mann= 7 ,-1 , 0
  4646.8     .07       0  4708.4    .035       0  4836.1     .07       0
  4988.2     .07       0  4992.2     .07       0  5213.2     .16       0
  5299.2     .07       0
Bank Sta=4988.2,4992.2
XS Rating Curve= 0 ,0
Exp/Cntr=0.3,0.1

Type RM Length L Ch R = 1 ,5813    ,316,316,316
BEGIN DESCRIPTION:
Sweetwater Creek Trib 14 4228
END DESCRIPTION:
XS GIS Cut Line= 3
      1366596.62      6830097.88      1366844.45      6829939.34
      1366854.88      6829626.91
#Sta/Elev= 30
  4705.8 2279.55  4733.5 2279.25  4739.5  2278.3  4761.4 2277.47  4775.8 2276.52
  4785.1 2277.27    4792 2275.85  4798.8  2276.6  4806.2 2275.14  4827.4 2273.05
  4834.5 2273.21  4870.1 2270.95    4906 2266.61  4915.3 2266.32  4929.4  2263.9
  4951.7 2261.93  4957.6 2258.94  4972.8 2260.25  4978.7 2256.42    4986 2256.32
  4986.3 2255.82    4990 2256.32  4997.4 2258.74  5011.3 2259.91  5021.3 2262.76
  5071.4    2268  5201.4  2274.3  5231.5 2276.46  5241.5  2276.2  5312.6 2279.56
#Mann= 5 ,-1 , 0
  4705.8     .07       0  4761.4    .035       0    4792     .07       0
    4986     .07       0    4990     .07       0
Bank Sta=4986,4990
XS Rating Curve= 0 ,0
Exp/Cntr=0.3,0.1

Type RM Length L Ch R = 1 ,5497    ,284,284,284
BEGIN DESCRIPTION:
Sweetwater Creek Trib 14 4227
END DESCRIPTION:
XS GIS Cut Line= 3
      1366893.91      6830269.34      1367105.01      6830087.99
      1367115.29      6829774.56
#Sta/Elev= 30
  4721.7 2271.49  4753.2 2270.59  4776.7 2269.89  4898.8 2264.79  4907.5 2264.64
    4972 2261.09  4986.3 2258.76  4996.7 2255.18  5002.5 2255.18    5008 2252.48
  5008.2 2251.98  5011.7 2251.98    5012 2252.48    5020 2253.66    5030 2257.29
    5040 2259.96    5050 2261.66    5060 2262.74  5075.1 2262.74    5080 2262.74
    5090  2264.3    5100 2266.94  5170.1 2271.15  5180.1 2272.74  5200.1 2272.49
  5240.1 2274.78  5260.1 2277.18  5270.1  2277.8  5290.1  2277.3  5313.6 2278.78
#Mann= 8 ,-1 , 0
  4721.7    .035       0  4753.2     .07       0  4776.7    .035       0
  4898.8     .07       0  4907.5     .16       0    5008     .07       0
    5012     .16       0  5075.1     .07       0
Bank Sta=5008,5012
XS Rating Curve= 0 ,0
Exp/Cntr=0.3,0.1

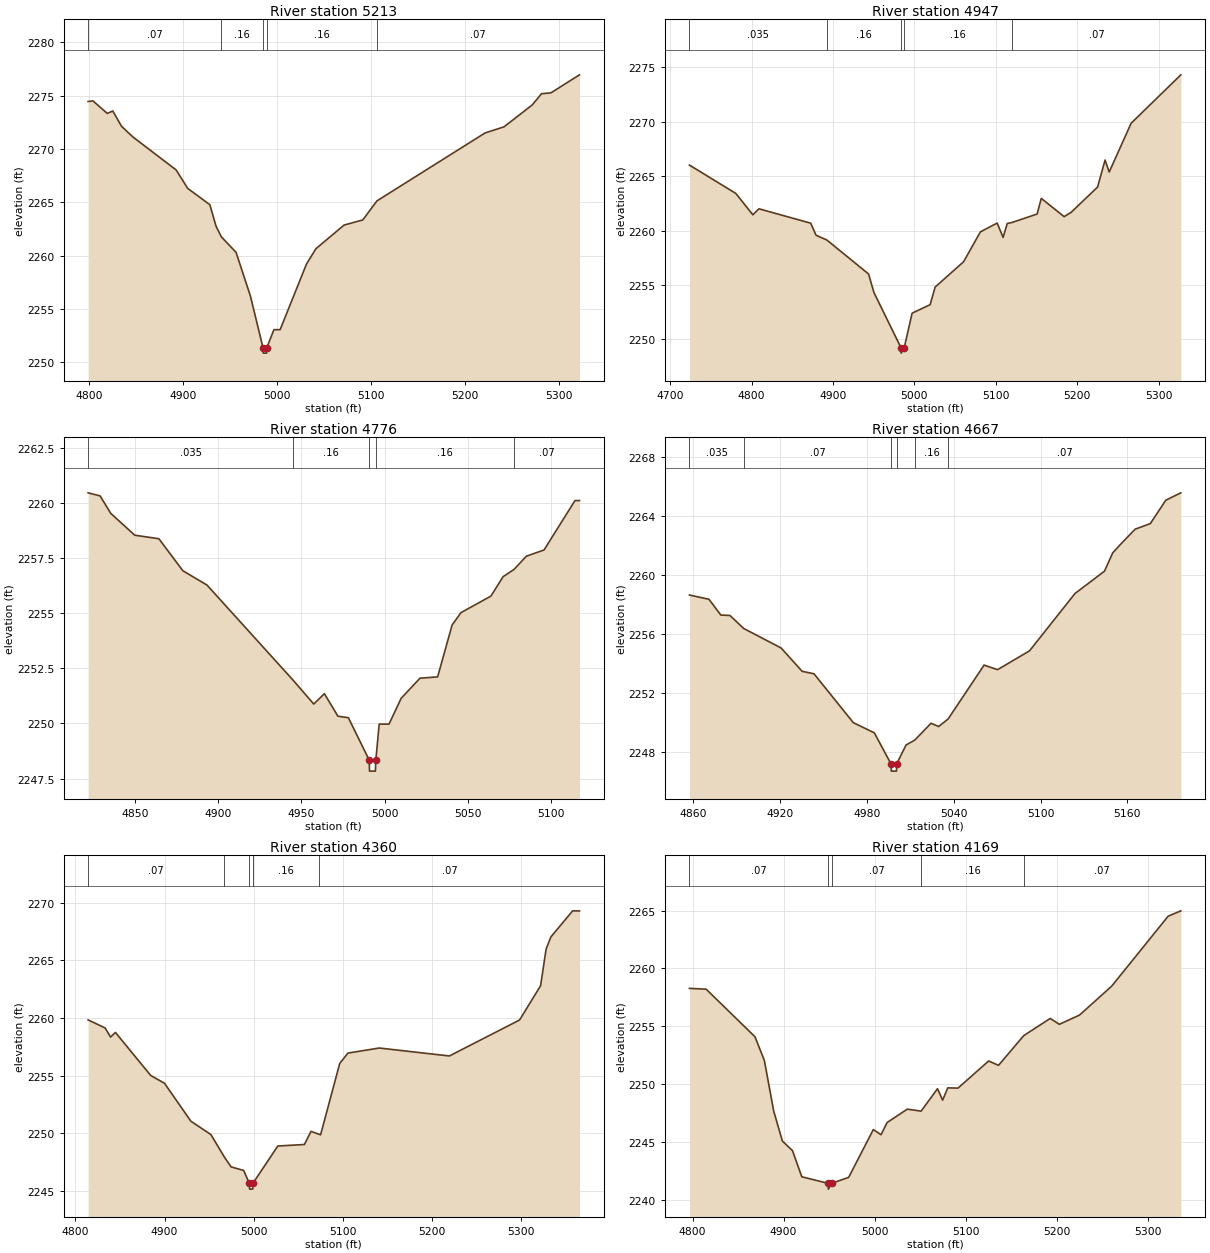
Type RM Length L Ch R = 1 ,5213    ,266,266,266
BEGIN DESCRIPTION:
Sweetwater Creek Trib 14 4226
END DESCRIPTION:
XS GIS Cut Line= 3
      1367134.87      6830395.16      1367306.05      6830289.06
      1367319.29      6829967.63
#Sta/Elev= 30
  4798.6 2274.45  4803.7 2274.51    4819 2273.33  4824.9 2273.56  4834.1 2272.13
  4846.2 2271.13  4892.3 2268.03  4904.6  2266.3  4928.2 2264.77  4934.8 2262.75
  4940.5 2261.75  4956.1  2260.3  4971.4  2256.2  4984.8 2251.35  4985.1 2250.85
  4988.6 2250.85  4988.8 2251.35  4996.4 2253.05    5003 2253.05  5031.1 2259.21
  5041.1 2260.64  5071.1 2262.86    5091 2263.34  5106.1 2265.13  5221.2  2271.5
  5241.3 2272.07  5271.3 2274.12  5281.3 2275.18  5291.3 2275.26  5321.7 2276.95
#Mann= 5 ,-1 , 0
  4798.6     .07       0  4940.5     .16       0  4984.8     .07       0
  4988.8     .16       0  5106.1     .07       0
Bank Sta=4984.8,4988.8
XS Rating Curve= 0 ,0
Exp/Cntr=0.3,0.1

Type RM Length L Ch R = 1 ,4947    ,171,171,171
BEGIN DESCRIPTION:
Sweetwater Creek Trib 14 4225
END DESCRIPTION:
XS GIS Cut Line= 3
      1367310.62       6830683.8      1367493.76      6830476.78
      1367571.03      6830158.63
#Sta/Elev= 30
  4723.6 2266.02  4780.6 2263.41  4801.5 2261.45    4809    2262  4872.6 2260.68
  4879.2 2259.57  4892.5 2259.13  4943.7 2256.01  4950.3 2254.31  4983.5 2249.24
  4983.7 2248.74  4987.5 2249.24  4997.2 2252.41  5019.3 2253.19  5025.5 2254.81
  5060.5 2257.14  5081.1 2259.88  5101.7 2260.69    5109 2259.37  5114.1 2260.65
  5119.8 2260.74  5150.8 2261.52  5155.9 2262.96    5184 2261.28  5192.5 2261.67
  5225.1    2264  5234.3 2266.48  5239.4 2265.38  5266.3 2269.86  5327.4 2274.31
#Mann= 5 ,-1 , 0
  4723.6    .035       0  4892.5     .16       0  4983.5     .07       0
  4987.5     .16       0  5119.8     .07       0
Bank Sta=4983.5,4987.5
XS Rating Curve= 0 ,0
Exp/Cntr=0.3,0.1

Type RM Length L Ch R = 1 ,4776    ,109,109,109
BEGIN DESCRIPTION:
Sweetwater Creek Trib 14 9.0
END DESCRIPTION:
XS GIS Cut Line= 3
      1367505.01      6830737.98      1367614.99      6830598.02
      1367655.01      6830487.97
#Sta/Elev= 30
    4822 2260.45  4829.2 2260.31  4835.6 2259.52    4850 2258.53  4864.5 2258.37
  4878.9 2256.92  4893.4 2256.27    4945 2251.97  4957.5 2250.88  4963.9 2251.35
    4972 2250.33  4978.3 2250.26  4990.8 2248.34    4991 2247.84  4994.5 2247.84
  4994.8 2248.34  4996.8 2249.97  5002.7 2249.97    5010 2251.14  5021.3 2252.05
  5031.9 2252.11  5040.6 2254.46  5045.9 2255.02  5063.9 2255.77  5071.2 2256.65
  5077.8 2256.98  5085.2 2257.58  5095.8 2257.86  5114.4  2260.1  5117.1  2260.1
#Mann= 5 ,-1 , 0
    4822    .035       0    4945     .16       0  4990.8     .07       0
  4994.8     .16       0  5077.8     .07       0
Bank Sta=4990.8,4994.8
XS Rating Curve= 0 ,0
Exp/Cntr=0.3,0.1

Type RM Length L Ch R = 1 ,4667    ,307,307,307
BEGIN DESCRIPTION:
Sweetwater Creek Trib 14 8.0
END DESCRIPTION:
XS GIS Cut Line= 3
      1367605.03      6830787.96       1367691.7       6830674.6
      1367754.99      6830488.04
#Sta/Elev= 30
  4857.3 2258.66  4870.8 2258.37    4879  2257.3  4885.3 2257.27  4894.8 2256.39
  4920.7 2255.06  4935.2 2253.48  4943.4 2253.31  4970.6 2249.99  4985.1  2249.3
  4996.6  2247.2  4996.9  2246.7  5000.4  2246.7  5000.6  2247.2    5007 2248.47
  5013.1 2248.81  5024.3 2249.95  5029.6 2249.73  5036.1 2250.24    5061  2253.9
  5070.3 2253.59  5092.4 2254.87  5123.8 2258.76  5144.2 2260.28  5149.9 2261.52
  5155.2 2262.09  5165.4 2263.13  5175.9 2263.51  5186.6  2265.1    5197  2265.6
#Mann= 6 ,-1 , 0
  4857.3    .035       0  4894.8     .07       0  4996.6     .07       0
  5000.6     .07       0  5013.1     .16       0  5036.1     .07       0
Bank Sta=4996.6,5000.6
XS Rating Curve= 0 ,0
Exp/Cntr=0.3,0.1

Type RM Length L Ch R = 1 ,4360    ,191,191,191
BEGIN DESCRIPTION:
Sweetwater Creek Trib 14 4224
END DESCRIPTION:
XS GIS Cut Line= 3
      1367898.73      6830905.13        1367980.      6830738.05
      1367846.62      6830397.32
#Sta/Elev= 30
  4814.2 2259.83  4833.3 2259.13  4839.4 2258.34  4844.9 2258.74  4884.5 2255.01
    4900 2254.33  4929.6 2251.04  4952.1 2249.88  4967.2 2247.93  4974.7 2247.08
  4988.9 2246.77  4995.2 2245.65  4995.5 2245.15    4999 2245.15  4999.2 2245.65
  5027.2 2248.89    5057 2249.02  5064.5 2250.16  5073.8  2249.9  5075.2 2249.86
  5096.7 2256.05  5105.9 2256.95  5141.1 2257.39  5219.8  2256.7  5298.6 2259.82
  5322.2 2262.79  5328.4 2265.97  5333.8 2267.03  5358.2 2269.29  5365.9 2269.28
#Mann= 5 ,-1 , 0
  4814.2     .07       0  4967.2     .16       0  4995.2     .07       0
  4999.2     .16       0  5073.8     .07       0
Bank Sta=4995.2,4999.2
XS Rating Curve= 0 ,0
Exp/Cntr=0.3,0.1

Type RM Length L Ch R = 1 ,4169    ,177,177,177
BEGIN DESCRIPTION:
Sweetwater Creek Trib 14 7.0
END DESCRIPTION:
XS GIS Cut Line= 3
        1368105.      6830887.99      1368152.72      6830690.27
      1368005.02      6830388.03
#Sta/Elev= 30
  4796.6 2258.27    4815  2258.2  4868.6 2254.08  4878.9 2252.03  4889.2 2247.64
  4898.7 2245.06  4909.8 2244.23    4920 2241.97  4948.9  2241.4  4949.2  2240.9
  4952.9  2241.4  4971.5 2241.92  4998.6 2246.05  5007.1 2245.61  5013.7 2246.66
  5035.9 2247.82  5051.1 2247.65  5069.1 2249.59  5074.7  2248.6  5080.4 2249.66
  5091.6 2249.64  5125.3 2251.99  5136.1 2251.61  5163.8 2254.18  5192.9 2255.67
  5202.9 2255.16  5225.1 2255.96  5260.4 2258.46  5322.4 2264.51  5336.4 2264.98
#Mann= 5 ,-1 , 0
  4796.6     .07       0  4948.9     .07       0  4952.9     .07       0
  5051.1     .16       0  5163.8     .07       0
Bank Sta=4948.9,4952.9
XS Rating Curve= 0 ,0
Exp/Cntr=0.3,0.1

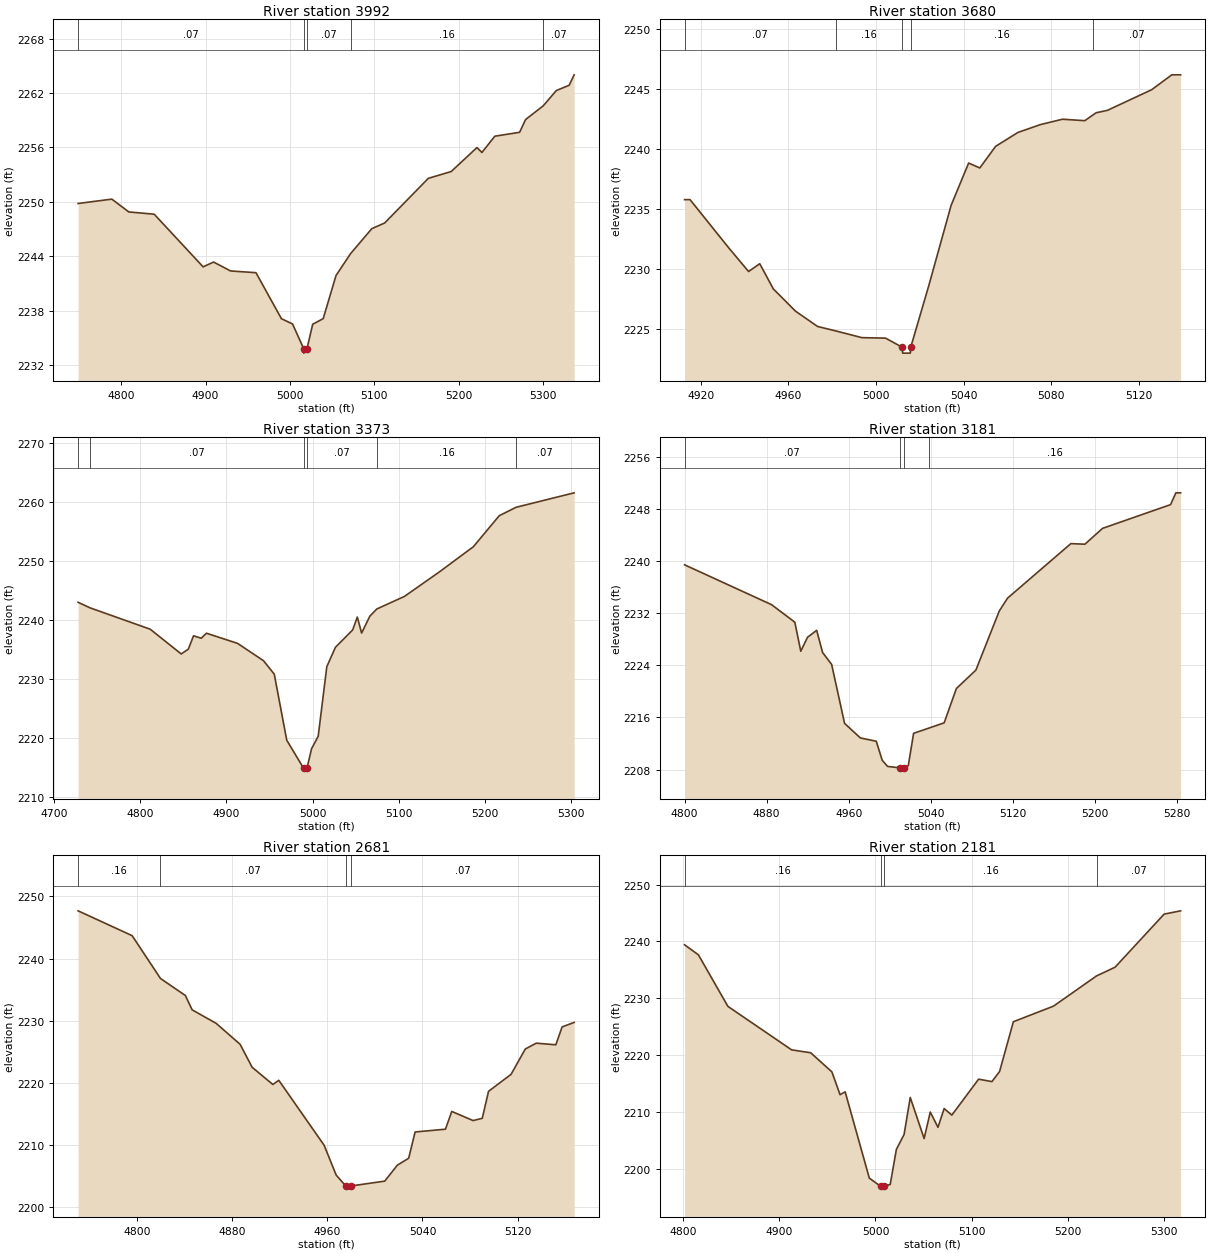
Type RM Length L Ch R = 1 ,3992    ,312,312,312
BEGIN DESCRIPTION:
Sweetwater Creek Trib 14 4223
END DESCRIPTION:
XS GIS Cut Line= 3
        1368285.       6830887.8      1368309.98      6830637.95
      1368129.78      6830353.41
#Sta/Elev= 30
  4748.9 2249.83  4788.9 2250.31    4809  2248.9  4839.1 2248.65  4897.1 2242.85
  4909.5 2243.38  4929.6  2242.4  4959.7 2242.21  4989.9 2237.14 5003.09 2236.56
  5016.2 2233.85  5016.4 2233.35  5020.2 2233.85 5026.94 2236.53  5039.4 2237.15
  5054.6  2241.9  5071.8  2244.3    5097 2247.06  5112.2 2247.68    5164  2252.6
  5191.1 2253.35  5221.6 2255.99  5227.5 2255.45  5242.8 2257.24  5272.2 2257.67
  5279.2 2259.07  5300.2 2260.59  5315.7 2262.27  5330.9 2262.85  5336.8    2264
#Mann= 5 ,-1 , 0
  4748.9     .07       0  5016.2     .07       0  5020.2     .07       0
  5071.8     .16       0  5300.2     .07       0
Bank Sta=5016.2,5020.2
XS Rating Curve= 0 ,0
Exp/Cntr=0.3,0.1

Type RM Length L Ch R = 1 ,3680    ,307,307,307
BEGIN DESCRIPTION:
Sweetwater Creek Trib 14 6.0
END DESCRIPTION:
XS GIS Cut Line= 3
        1368605.      6830738.02      1368618.17      6830651.72
      1368593.09        6830515.
#Sta/Elev= 30
  4912.7 2235.74  4915.2 2235.74    4933 2231.69  4941.9 2229.75    4947  2230.4
  4953.2  2228.3  4963.3 2226.45  4973.4 2225.17  4981.7  2224.8  4993.6 2224.24
  5004.4  2224.2  5011.9 2223.45  5012.2 2222.95  5015.7 2222.95  5015.9 2223.45
  5024.1 2228.56  5034.3 2235.26  5042.3 2238.79  5047.4 2238.38  5054.6 2240.18
  5064.8 2241.34    5075 2241.99  5085.1 2242.44  5095.3 2242.32  5099.2 2242.82
  5100.5 2242.98  5105.6 2243.18  5125.8  2244.9    5135 2246.14    5139 2246.14
#Mann= 5 ,-1 , 0
  4912.7     .07       0  4981.7     .16       0  5011.9     .07       0
  5015.9     .16       0  5099.2     .07       0
Bank Sta=5011.9,5015.9
XS Rating Curve= 0 ,0
Exp/Cntr=0.3,0.1

Type RM Length L Ch R = 1 ,3373    ,192,192,192
BEGIN DESCRIPTION:
Sweetwater Creek Trib 14 4218
END DESCRIPTION:
XS GIS Cut Line= 3
      1368645.28      6830955.05      1368872.05      6830804.49
      1368860.16      6830501.13
#Sta/Elev= 30
  4727.8 2242.96  4741.6 2242.02  4811.5  2238.4  4847.5 2234.21  4855.8 2235.03
  4861.8 2237.28  4870.8 2236.87  4876.8 2237.72  4912.9    2236    4943 2233.07
  4955.5 2230.79    4970 2219.61  4989.5 2214.87  4989.8 2214.37  4993.5 2214.87
  4998.8 2218.16  5006.5 2220.26  5016.5 2232.05  5026.5 2235.33  5046.5 2238.27
  5051.9 2240.45  5056.9 2237.75  5066.5 2240.61  5074.5 2241.82  5106.6 2243.95
  5146.6 2248.04  5186.6 2252.36  5216.7 2257.62  5236.2 2259.04  5303.6 2261.49
#Mann= 6 ,-1 , 0
  4727.8     .16       0  4741.6     .07       0  4989.5     .07       0
  4993.5     .07       0  5074.5     .16       0  5236.2     .07       0
Bank Sta=4989.5,4993.5
XS Rating Curve= 0 ,0
Exp/Cntr=0.3,0.1

Type RM Length L Ch R = 1 ,3181    ,500,500,500
BEGIN DESCRIPTION:
Sweetwater Creek Trib 14 5.0
END DESCRIPTION:
XS GIS Cut Line= 3
       1368851.5      6831140.46      1368955.49      6830969.62
      1369022.47      6830694.04
#Sta/Elev= 30
    4800  2239.4  4884.8 2233.29  4907.5  2230.6  4913.3 2226.15  4919.9 2228.29
  4928.8 2229.35  4934.6 2225.94  4943.4 2224.12    4956 2215.08  4971.4 2212.85
  4986.9 2212.34  4992.7 2209.42    4998 2208.48    5010 2208.26  5010.2 2207.76
    5014 2208.26  5018.1 2208.59  5023.3 2213.56  5038.6 2214.38  5053.1 2215.17
    5065 2220.43    5084 2223.25  5106.8 2232.31  5114.9 2234.29  5176.6 2242.65
  5190.3 2242.56  5207.5 2244.99  5273.8 2248.63    5279 2250.44  5283.6 2250.44
#Mann= 4 ,-1 , 0
    4800     .07       0    5010     .07       0    5014     .07       0
  5038.6     .16       0
Bank Sta=5010,5014
XS Rating Curve= 0 ,0
Exp/Cntr=0.3,0.1

Type RM Length L Ch R = 1 ,2681    ,500,500,500
BEGIN DESCRIPTION:
Sweetwater Creek Trib 14 4.0
END DESCRIPTION:
XS GIS Cut Line= 3
       1369328.3      6831342.96      1369360.92      6831095.81
      1369305.01      6830938.02
#Sta/Elev= 30
  4750.7 2247.69  4796.1 2243.69  4819.9  2236.8  4840.8 2234.06  4846.5 2231.75
  4866.7 2229.57  4886.8  2226.2  4896.9  2222.5  4914.3 2219.73  4919.3  2220.4
  4957.4 2209.94  4967.5 2205.14  4975.6 2203.38  4975.9 2202.88  4979.6 2203.38
  5008.3 2204.17  5018.9 2206.74  5028.4 2207.85  5033.8 2212.08  5059.3 2212.53
  5064.6 2215.39  5082.5 2213.92  5090.2 2214.28  5095.5 2218.63  5114.4 2221.36
  5126.4 2225.45  5135.6 2226.38    5152 2226.12  5157.3    2229  5167.4 2229.72
#Mann= 4 ,-1 , 0
  4750.7     .16       0  4819.9     .07       0  4975.6     .07       0
  4979.6     .07       0
Bank Sta=4975.6,4979.6
XS Rating Curve= 0 ,0
Exp/Cntr=0.3,0.1

Type RM Length L Ch R = 1 ,2181    ,496,496,496
BEGIN DESCRIPTION:
Sweetwater Creek Trib 14 3.0
END DESCRIPTION:
XS GIS Cut Line= 3
      1369491.48      6831429.97      1369677.52      6831361.33
      1369876.47      6831114.66
#Sta/Elev= 30
  4801.7  2239.4  4816.1 2237.63  4846.7 2228.56  4912.9  2220.9  4932.7 2220.39
  4954.7 2217.03  4963.2 2213.01  4968.5 2213.51  4993.6 2198.32  5005.3 2196.88
  5005.6 2196.38  5009.3 2196.88  5015.3 2197.21  5021.7 2203.38  5029.7    2206
  5036.1 2212.52  5050.5 2205.29  5056.9 2209.95  5064.9 2207.26  5071.3 2210.57
  5079.3 2209.41  5107.1 2215.74  5120.9 2215.31  5128.9 2217.09  5143.2 2225.85
  5184.9  2228.6  5229.6 2233.92  5248.8 2235.45  5299.8  2244.8  5316.9 2245.38
#Mann= 4 ,-1 , 0
  4801.7     .16       0  5005.3     .07       0  5009.3     .16       0
  5229.6     .07       0
Bank Sta=5005.3,5009.3
XS Rating Curve= 0 ,0
Exp/Cntr=0.3,0.1

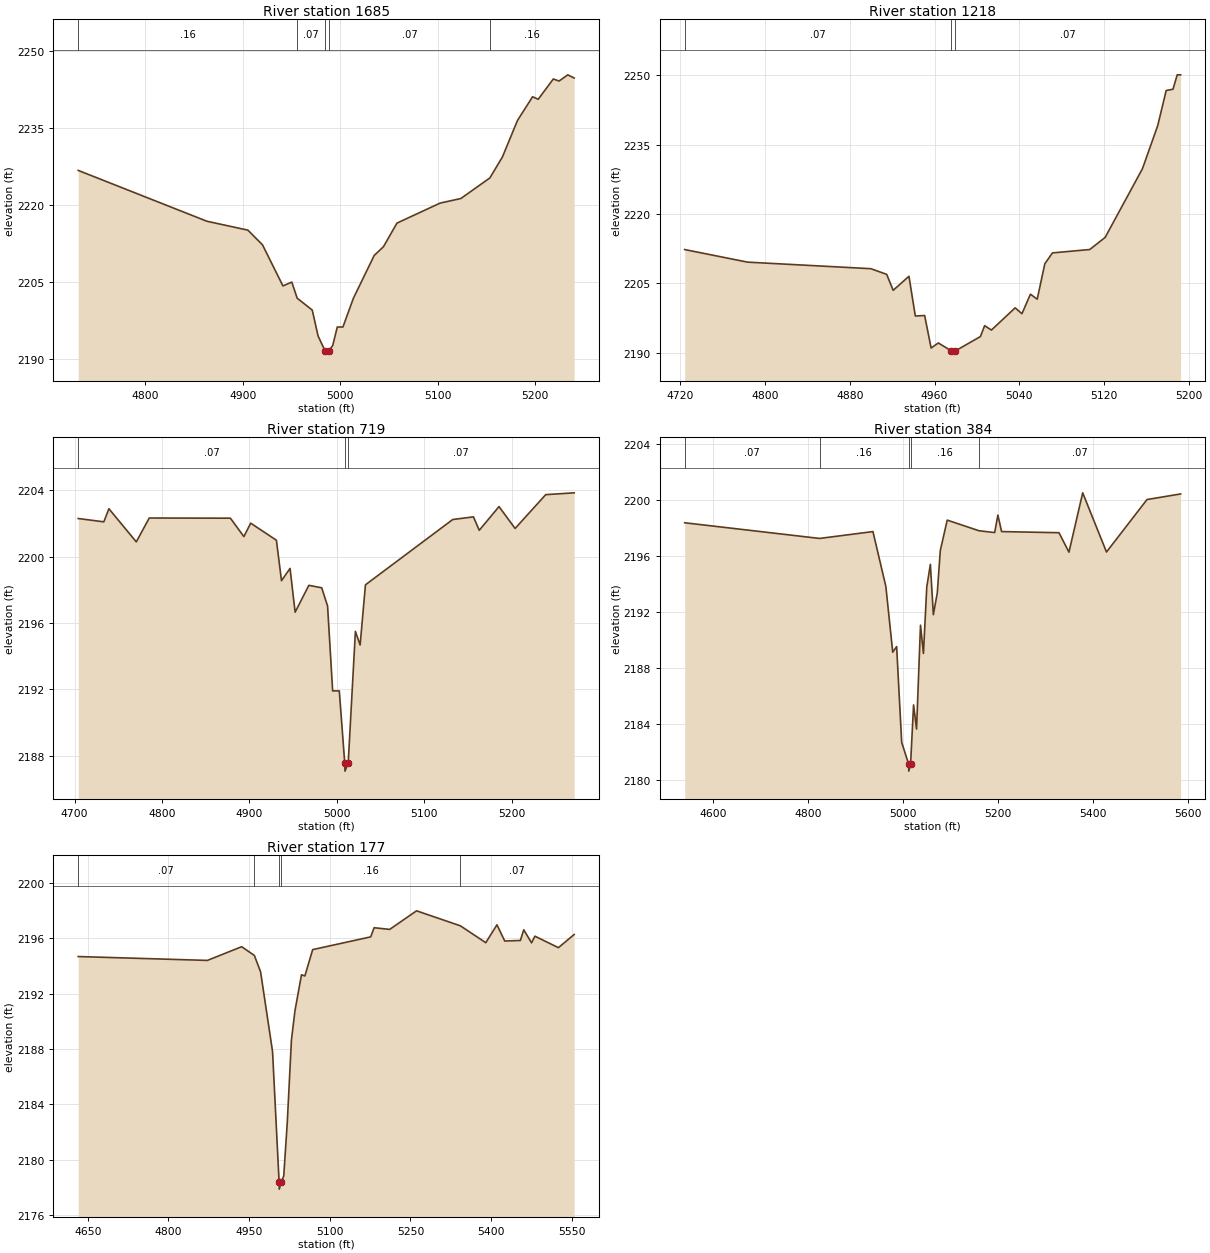
Type RM Length L Ch R = 1 ,1685    ,467,467,467
BEGIN DESCRIPTION:
Sweetwater Creek Trib 14 2.0
END DESCRIPTION:
XS GIS Cut Line= 3
      1369791.06      6831847.01      1370015.05      6831697.87
      1370139.67      6831492.41
#Sta/Elev= 30
  4730.9 2226.76  4863.1 2216.87  4905.2 2215.14  4920.2 2212.28  4941.2 2204.29
  4950.3 2205.04  4955.8 2201.91  4971.3 2199.59  4977.3 2194.55  4984.3 2191.72
  4984.6 2191.22  4988.3 2191.72  4992.3 2192.68    4997  2196.3  5002.8  2196.3
  5013.5 2201.87  5034.9 2210.21  5044.4 2211.91  5058.3 2216.51  5102.6  2220.4
  5123.9 2221.29  5153.7 2225.29  5166.6 2229.36  5182.1 2236.48  5197.6 2241.08
  5203.4  2240.6  5218.9 2244.54  5224.8 2244.14  5233.8 2245.35  5240.3 2244.73
#Mann= 5 ,-1 , 0
  4730.9     .16       0  4955.8     .07       0  4984.3     .07       0
  4988.3     .07       0  5153.7     .16       0
Bank Sta=4984.3,4988.3
XS Rating Curve= 0 ,0
Exp/Cntr=0.3,0.1

Type RM Length L Ch R = 1 ,1218    ,499,499,499
BEGIN DESCRIPTION:
Sweetwater Creek Trib 14 1.0
END DESCRIPTION:
XS GIS Cut Line= 3
      1370157.85      6832094.39      1370384.96      6831938.09
      1370505.01      6831787.99
#Sta/Elev= 30
  4724.3 2212.31  4783.6 2209.59    4900 2208.17  4914.9 2206.94    4921 2203.49
  4935.9 2206.53  4941.9 2197.93  4950.7 2198.04  4956.8 2191.01  4963.6  2192.1
  4975.8  2190.4    4976  2189.9  4979.8  2190.4  5003.3 2193.48  5007.3 2195.84
  5013.7 2194.89  5036.1  2199.7  5042.5 2198.43  5050.5 2202.65  5056.9 2201.57
  5064.1 2209.24  5071.3 2211.59  5106.5 2212.32    5121 2214.94  5156.2 2229.81
  5170.6 2239.13  5178.6 2246.73    5185    2247    5189 2250.12  5192.2 2250.12
#Mann= 3 ,-1 , 0
  4724.3     .07       0  4975.8     .07       0  4979.8     .07       0
Bank Sta=4975.8,4979.8
XS Rating Curve= 0 ,0
Exp/Cntr=0.3,0.1

Type RM Length L Ch R = 1 ,719     ,335,335,335
BEGIN DESCRIPTION:
Sweetwater Creek Trib 14 903
END DESCRIPTION:
XS GIS Cut Line= 3
      1370554.99        6832288.      1370809.97      6832138.06
        1370705.        6831888.
#Sta/Elev= 30
  4704.2  2202.3  4733.5  2202.1  4739.3 2202.89  4770.6 2200.89  4785.4 2202.33
  4878.2 2202.32  4893.6 2201.21  4901.4 2202.02  4930.8 2200.99  4936.6 2198.55
  4946.4 2199.29  4952.2 2196.65  4967.9 2198.27  4982.6 2198.12  4989.3 2197.02
  4995.1  2191.9  5002.7  2191.9  5008.9 2187.56  5009.2 2187.06  5012.9 2187.56
  5021.1 2195.49  5026.5 2194.67  5032.6  2198.3  5132.4 2202.24  5156.1  2202.4
  5162.7 2201.59  5185.3 2203.02  5203.7  2201.7  5238.7 2203.74  5271.2 2203.85
#Mann= 3 ,-1 , 0
  4704.2     .07       0  5008.9     .07       0  5012.9     .07       0
Bank Sta=5008.9,5012.9
XS Rating Curve= 0 ,0
Exp/Cntr=0.3,0.1

Type RM Length L Ch R = 1 ,384     ,207,207,207
BEGIN DESCRIPTION:
Sweetwater Creek Trib 14 4374
END DESCRIPTION:
XS GIS Cut Line= 3
      1370768.81      6832446.78      1371135.12      6832167.72
      1370785.24       6831699.5
#Sta/Elev= 30
  4539.5 2198.38  4823.8 2197.26  4936.2 2197.75  4963.4 2193.83  4977.9 2189.13
  4986.1 2189.53  4996.8 2182.68  5011.5 2181.13  5011.7 2180.63  5015.5 2181.13
  5021.8 2185.36  5028.1 2183.64  5036.4 2191.06  5042.6 2189.04  5049.6 2193.78
  5057.2 2195.41  5063.5 2191.81  5071.8 2193.37  5078.1 2196.39  5092.7 2198.57
  5159.6 2197.81  5192.7 2197.68  5199.4 2198.93  5207.3 2197.75  5328.2 2197.67
  5349.2 2196.28  5378.2 2200.52  5428.3 2196.29  5513.7 2200.04  5584.5 2200.44
#Mann= 5 ,-1 , 0
  4539.5     .07       0  4823.8     .16       0  5011.5     .07       0
  5015.5     .16       0  5159.6     .07       0
Bank Sta=5011.5,5015.5
XS Rating Curve= 0 ,0
Exp/Cntr=0.3,0.1

Type RM Length L Ch R = 1 ,177     ,0,0,0
BEGIN DESCRIPTION:
Sweetwater Creek Trib 14 4373
END DESCRIPTION:
XS GIS Cut Line= 3
      1371015.36      6832516.21      1371333.05      6832254.07
      1371022.29      6831849.55
#Sta/Elev= 30
  4632.3 2194.68  4872.4  2194.4  4936.2 2195.39  4959.8 2194.76  4971.4 2193.57
  4993.6 2187.82  5005.8 2178.39  5006.1 2177.89  5009.8 2178.39  5014.4 2178.84
  5020.9 2182.65  5028.7 2188.65  5035.2 2190.75  5047.4 2193.36  5053.7 2193.28
  5068.2 2195.18  5176.1  2196.1  5182.4 2196.76  5211.4 2196.64  5261.3 2197.98
  5342.7  2196.9    5390 2195.68  5410.8 2196.97  5425.3  2195.8  5454.3 2195.84
  5460.6 2196.61  5475.1 2195.67  5481.4 2196.15    5525 2195.32  5554.3 2196.27
#Mann= 5 ,-1 , 0
  4632.3     .07       0  4959.8     .16       0  5005.8     .07       0
  5009.8     .16       0  5342.7     .07       0
Bank Sta=5005.8,5009.8
XS Rating Curve= 0 ,0
Exp/Cntr=0.3,0.1

Chan Stop Cuts=-1
Use User Specified Reach Order=0
Composite Channel Slope=5