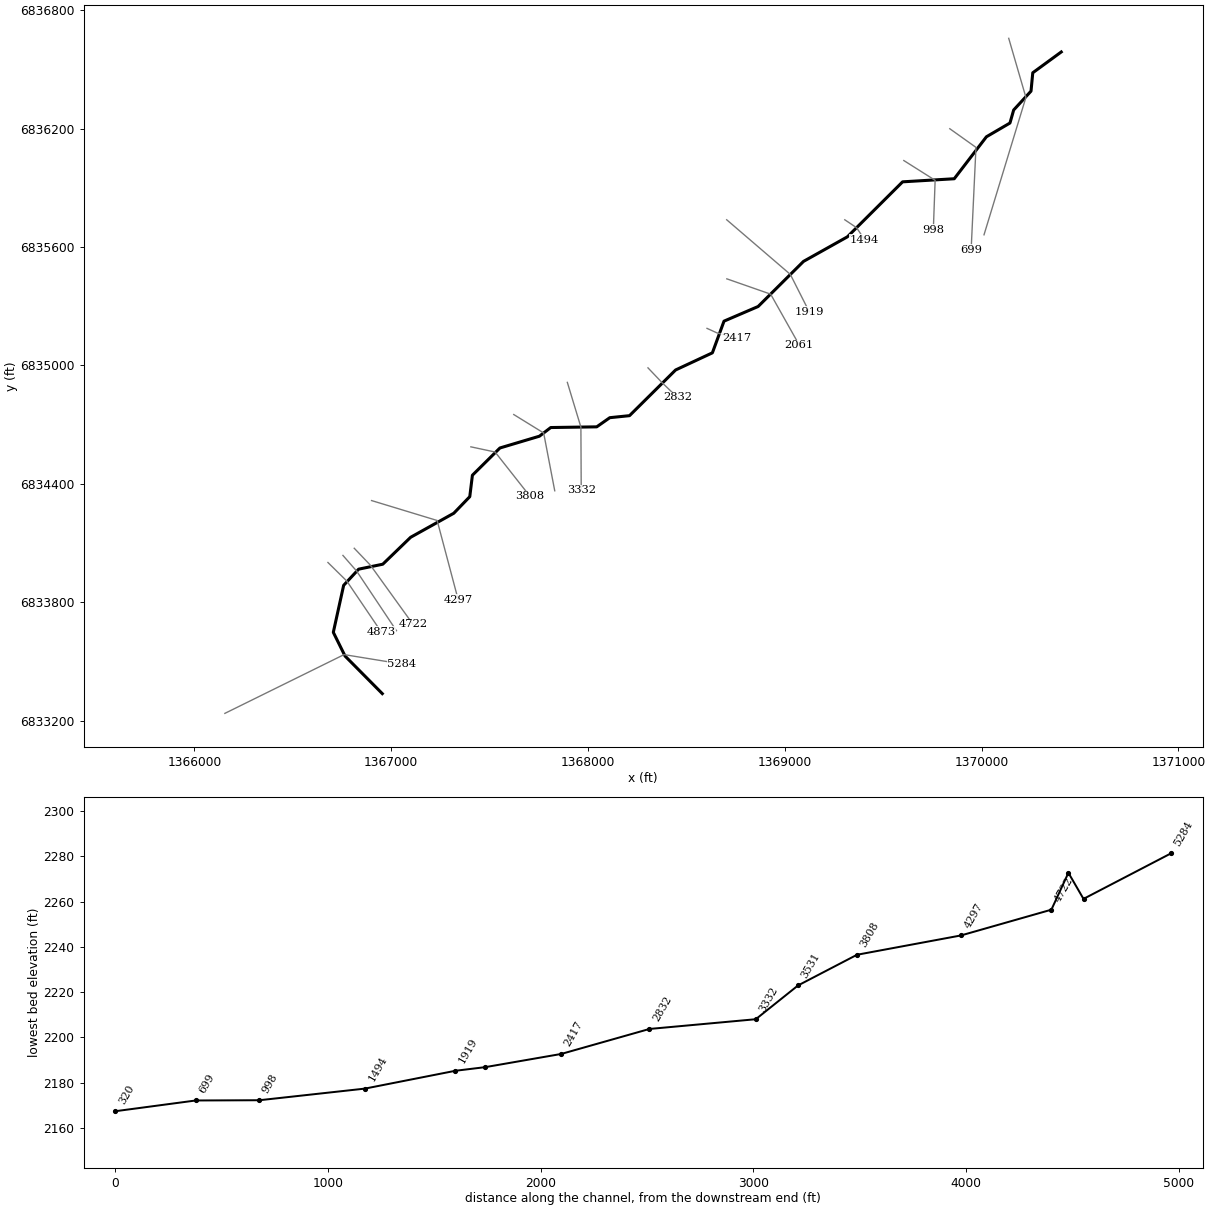
--- Sweetwater Creek Trib 15.prj (project) ---

Proj Title=Sweetwater Creek Trib 15 Base Level Engineering
Current Plan=p01
Default Exp/Contr=0.3,0.1
English Units
Geom File=g01
Flow File=f01
Plan File=p01
Y Axis Title=Elevation
X Axis Title(PF)=Main Channel Distance
X Axis Title(XS)=Station
BEGIN DESCRIPTION:
Sweetwater Creek Trib 15
END DESCRIPTION:
DSS Export Rating Curves= 0
DSS Export Rating Curve Sorted= 0
DSS Export Volume Flow Curves= 0
DXF OffsetX= 0
DXF OffsetY= 0
DXF ScaleX= 1
DXF ScaleY= 10

--- Sweetwater Creek Trib 15.p01 (plan) ---

Plan Title=Multiple Run
Short Identifier=Multiple
Geom File=g01
Flow File=f01
Subcritical Flow
K Sum by GR= 0
Std Step Tol= 0.01
Critical Tol= 0.01
Num of Std Step Trials= 20
Max Error Tol= 0.3
Flow Tol Ratio= 0.001
Split Flow NTrial= 30
Split Flow Tol= 0.02
Split Flow Ratio= 0.02
Log Output Level= 0
Friction Slope Method= 1
Unsteady Friction Slope Method= 2
Unsteady Bridges Friction Slope Method= 1
Parabolic Critical Depth
Global Vel Dist=  1 , 1 , 1
Global Log Level= 0
CheckData=True
Encroach Param= -1, 0, 0, 0
BEGIN DESCRIPTION:
Multiple Run
END DESCRIPTION:

--- Sweetwater Creek Trib 15.f01 (steady flow) ---

Flow Title=Multiple
Program Version=4.10
Number of Profiles= 7
Profile Names=10-year,25-year,50-year,1pct_min,100-year,1pct_plu,500-year
River Rch & RM=Sweetwater Creek,Reach-1         ,5284
     167     232     286     176     352     702     537
Boundary for River Rch & Prof#=Sweetwater Creek,Reach-1         , 1
Up Type= 0
Dn Type= 3
Dn Slope=0.012
Boundary for River Rch & Prof#=Sweetwater Creek,Reach-1         , 2
Up Type= 0
Dn Type= 3
Dn Slope=0.012
Boundary for River Rch & Prof#=Sweetwater Creek,Reach-1         , 3
Up Type= 0
Dn Type= 3
Dn Slope=0.012
Boundary for River Rch & Prof#=Sweetwater Creek,Reach-1         , 4
Up Type= 0
Dn Type= 3
Dn Slope=0.012
Boundary for River Rch & Prof#=Sweetwater Creek,Reach-1         , 5
Up Type= 0
Dn Type= 3
Dn Slope=0.012
Boundary for River Rch & Prof#=Sweetwater Creek,Reach-1         , 6
Up Type= 0
Dn Type= 3
Dn Slope=0.012
Boundary for River Rch & Prof#=Sweetwater Creek,Reach-1         , 7
Up Type= 0
Dn Type= 3
Dn Slope=0.012
DSS Import GetInterval= 0
DSS Import GetPeak= 0
DSS Import FillOption= 0

--- Sweetwater Creek Trib 15.g01 (geometry) ---

Geom Title=Existing Conditions
Program Version=4.10

River Reach=Sweetwater Creek,Reach-1
Reach XY= 30
        1366955.        6833338.      1366765.76      6833528.32
      1366706.08      6833648.54      1366758.61      6833886.52
       1366834.8      6833968.39      1366957.43      6833993.52
      1367098.95      6834129.84      1367318.24      6834251.62
      1367399.48      6834335.56      1367412.86      6834444.17
       1367552.7      6834582.17       1367753.4      6834641.86
      1367810.94      6834685.74       1368044.5      6834689.22
      1368110.98      6834735.64      1368211.17      6834745.86
      1368445.32      6834977.24      1368632.28       6835064.1
      1368691.37      6835224.55      1368864.68      6835298.76
      1369095.32      6835527.22      1369318.21      6835651.63
      1369598.81      6835930.19      1369861.21       6835945.8
      1370024.77      6836158.41      1370144.35        6836228.
      1370163.19      6836294.02      1370251.35      6836389.57
      1370260.25      6836482.54        1370405.        6836588.

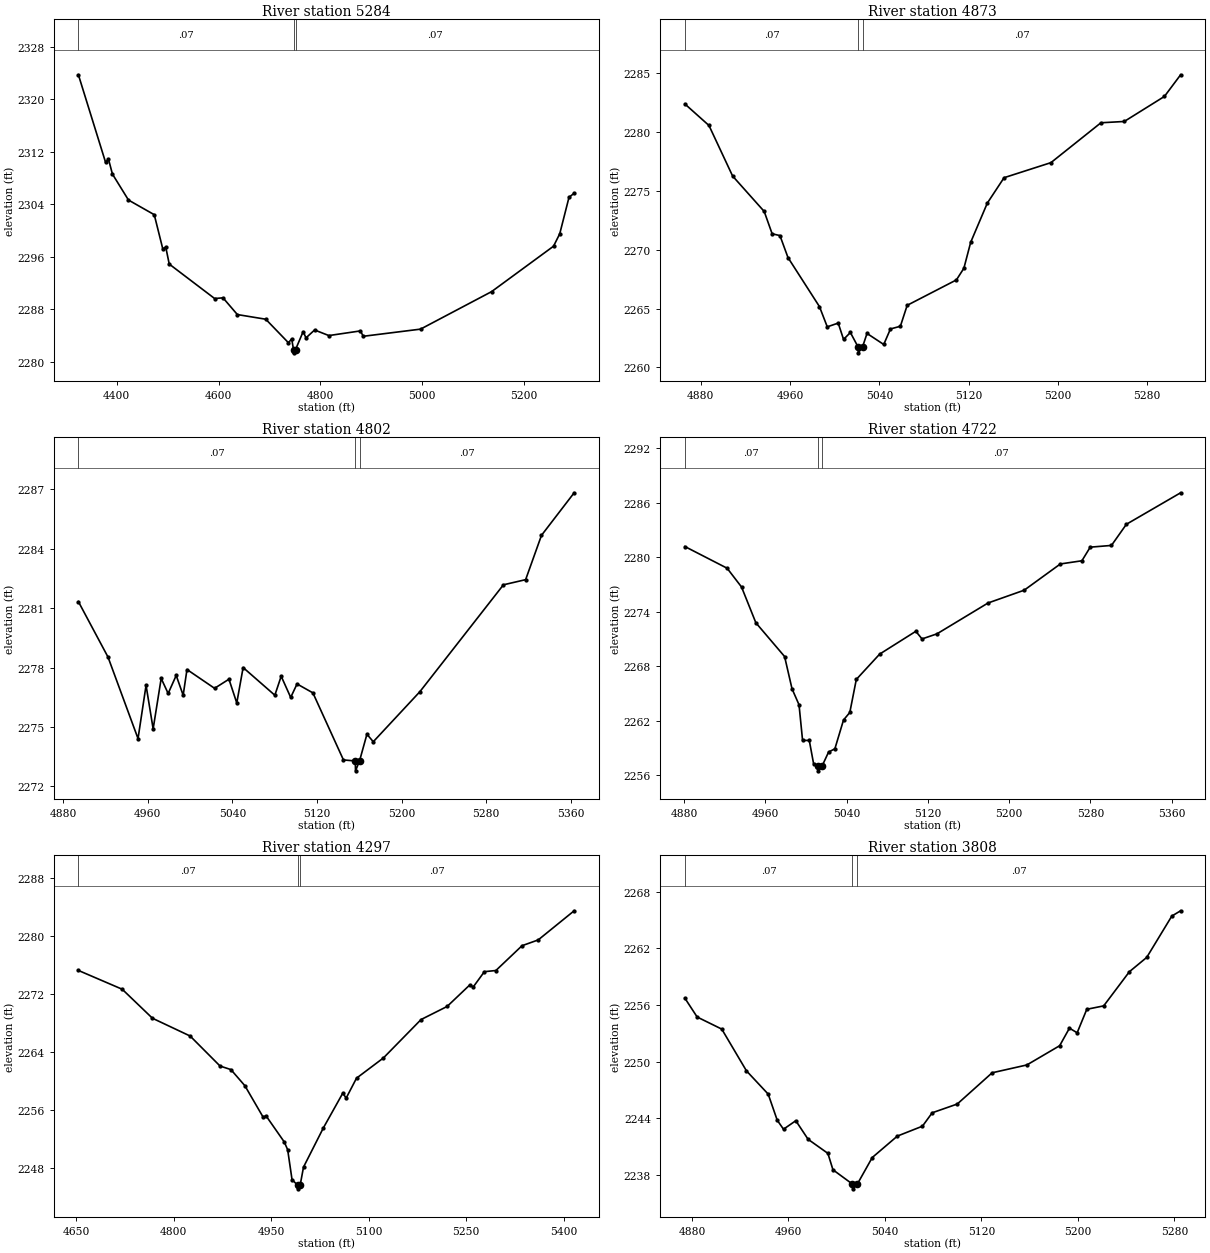
Type RM Length L Ch R = 1 ,5284    ,411,411,411
BEGIN DESCRIPTION:
Sweetwater Creek Trib 15 10.0
END DESCRIPTION:
XS GIS Cut Line= 3
      1366155.02      6833238.01      1366760.83       6833535.7
      1367054.99        6833488.
#Sta/Elev= 30
    4325 2323.71  4378.4 2310.36    4384 2310.88  4391.8 2308.59  4423.3 2304.63
  4473.9  2302.4  4490.8 2297.14  4496.4 2297.49  4503.3 2294.88  4592.4 2289.63
  4608.8 2289.74    4637 2287.19  4692.7 2286.48  4737.2  2282.9  4743.6 2283.48
  4747.2 2281.86  4747.5 2281.36  4751.2 2281.86  4766.1 2284.59  4771.7 2283.64
  4788.6 2284.84  4816.6 2283.99  4878.5  2284.7  4884.1 2283.88  4996.5 2284.97
  5135.9 2290.68  5257.5  2297.6  5269.7 2299.49  5287.9 2305.05    5298 2305.67
#Mann= 3 ,-1 , 0
    4325     .07       0  4747.2     .07       0  4751.2     .07       0
Bank Sta=4747.2,4751.2
XS Rating Curve= 0 ,0
Exp/Cntr=0.3,0.1

Type RM Length L Ch R = 1 ,4873    ,71,71,71
BEGIN DESCRIPTION:
Sweetwater Creek Trib 15 4146
END DESCRIPTION:
XS GIS Cut Line= 3
      1366678.71      6834002.23      1366774.61       6833908.2
      1366948.75      6833651.85
#Sta/Elev= 30
  4865.7  2282.4  4887.3 2280.57  4908.5 2276.27  4936.8 2273.26  4943.9 2271.36
  4950.9 2271.21  4958.1 2269.34  4986.3 2265.17  4993.3 2263.45  5003.1 2263.77
  5007.9 2262.38    5014 2262.97  5020.9 2261.74  5021.1 2261.24  5024.9 2261.74
  5028.9 2262.89  5043.9 2261.95  5049.9 2263.27  5058.8  2263.5  5064.9 2265.28
    5109 2267.44  5115.7 2268.43  5121.8 2270.64  5136.7 2273.97  5151.7 2276.13
  5193.7 2277.41  5238.5  2280.8  5259.4 2280.91  5295.4 2283.04  5309.9 2284.88
#Mann= 3 ,-1 , 0
  4865.7     .07       0  5020.9     .07       0  5024.9     .07       0
Bank Sta=5020.9,5024.9
XS Rating Curve= 0 ,0
Exp/Cntr=0.3,0.1

Type RM Length L Ch R = 1 ,4802    ,80,80,80
BEGIN DESCRIPTION:
Sweetwater Creek Trib 15 9.0
END DESCRIPTION:
XS GIS Cut Line= 3
      1366755.02      6834037.98      1366824.72      6833958.51
      1367026.81      6833656.73
#Sta/Elev= 30
  4894.3 2281.33  4922.3 2278.53  4950.7 2274.41  4958.3  2277.1    4965  2274.9
  4972.6 2277.45  4979.2 2276.69  4986.8  2277.6  4993.4  2276.6    4997  2277.9
  5023.1 2276.95  5036.7 2277.41  5044.1 2276.21  5050.1    2278  5080.1  2276.6
  5086.1 2277.56  5095.1 2276.49  5101.1 2277.17  5116.1 2276.72    5145 2273.33
  5156.2 2273.28  5156.4 2272.78  5160.2 2273.28  5167.2 2274.63  5173.2 2274.25
  5217.3 2276.78  5296.3 2282.18  5317.3 2282.44  5332.3 2284.68  5363.2 2286.83
#Mann= 3 ,-1 , 0
  4894.3     .07       0  5156.2     .07       0  5160.2     .07       0
Bank Sta=5156.2,5160.2
XS Rating Curve= 0 ,0
Exp/Cntr=0.3,0.1

Type RM Length L Ch R = 1 ,4722    ,425,425,425
BEGIN DESCRIPTION:
Sweetwater Creek Trib 15 4009
END DESCRIPTION:
XS GIS Cut Line= 3
      1366812.38      6834074.29      1366894.93      6833988.16
      1367110.97      6833689.25
#Sta/Elev= 30
  4880.7 2281.17  4922.3 2278.78  4936.5 2276.71  4950.6 2272.77  4978.9 2269.05
  4986.2  2265.5  4993.1 2263.74  4996.6 2259.81  5003.2 2259.81  5007.5 2257.21
  5011.7 2256.96  5011.9 2256.46  5015.7 2256.96  5022.2 2258.53  5028.4 2258.89
  5036.9 2262.06  5043.1 2262.89  5049.5 2266.53  5072.5 2269.32  5108.1 2271.83
  5114.2 2270.99  5128.9 2271.55  5179.2 2274.95  5214.8 2276.36  5250.4 2279.25
  5271.6  2279.6  5279.8  2281.1  5300.7 2281.29  5315.4 2283.62  5368.8 2287.09
#Mann= 3 ,-1 , 0
  4880.7     .07       0  5011.7     .07       0  5015.7     .07       0
Bank Sta=5011.7,5015.7
XS Rating Curve= 0 ,0
Exp/Cntr=0.3,0.1

Type RM Length L Ch R = 1 ,4297    ,489,489,489
BEGIN DESCRIPTION:
Sweetwater Creek Trib 15 8.0
END DESCRIPTION:
XS GIS Cut Line= 3
      1366900.46      6834315.87      1367233.73      6834214.94
       1367340.4      6833814.52
#Sta/Elev= 30
  4653.5 2275.27  4720.9 2272.67  4767.4 2268.66  4825.4  2266.2  4871.4 2262.05
  4888.1 2261.56  4909.6 2259.33  4937.3 2255.04  4942.5 2255.12  4970.2 2251.55
  4975.4 2250.48  4982.1 2246.36  4990.6 2245.57  4990.8 2245.07  4994.6 2245.57
  4999.8 2248.08  5030.4 2253.51  5060.2  2258.3  5065.4 2257.62  5081.3 2260.37
  5122.7 2263.17  5180.6 2268.48  5220.7 2270.29  5255.6 2273.27  5260.8 2272.98
    5278  2275.1  5295.7 2275.26  5335.9 2278.69  5360.8 2279.49  5416.1 2283.52
#Mann= 3 ,-1 , 0
  4653.5     .07       0  4990.6     .07       0  4994.6     .07       0
Bank Sta=4990.6,4994.6
XS Rating Curve= 0 ,0
Exp/Cntr=0.3,0.1

Type RM Length L Ch R = 1 ,3808    ,277,277,277
BEGIN DESCRIPTION:
Sweetwater Creek Trib 15 7.0
END DESCRIPTION:
XS GIS Cut Line= 3
      1367405.05      6834587.99      1367528.18      6834561.71
      1367705.03      6834337.96
#Sta/Elev= 30
  4874.1 2256.73  4884.3 2254.73  4904.7 2253.45  4925.2 2249.02  4943.2 2246.56
  4950.7 2243.79  4955.9 2242.84  4966.1 2243.74  4976.3 2241.77  4992.7 2240.28
  4996.9 2238.54  5013.1 2237.02  5013.3 2236.52  5017.1 2237.02  5029.5 2239.84
  5050.3 2242.11  5071.1 2243.16  5079.2 2244.58    5100 2245.51  5128.9 2248.82
  5157.7 2249.65  5184.9 2251.69    5193 2253.55  5199.4 2253.06  5207.4 2255.55
  5221.4 2255.91  5242.7 2259.53  5257.1 2261.05  5277.9 2265.43  5285.2 2265.99
#Mann= 3 ,-1 , 0
  4874.1     .07       0  5013.1     .07       0  5017.1     .07       0
Bank Sta=5013.1,5017.1
XS Rating Curve= 0 ,0
Exp/Cntr=0.3,0.1

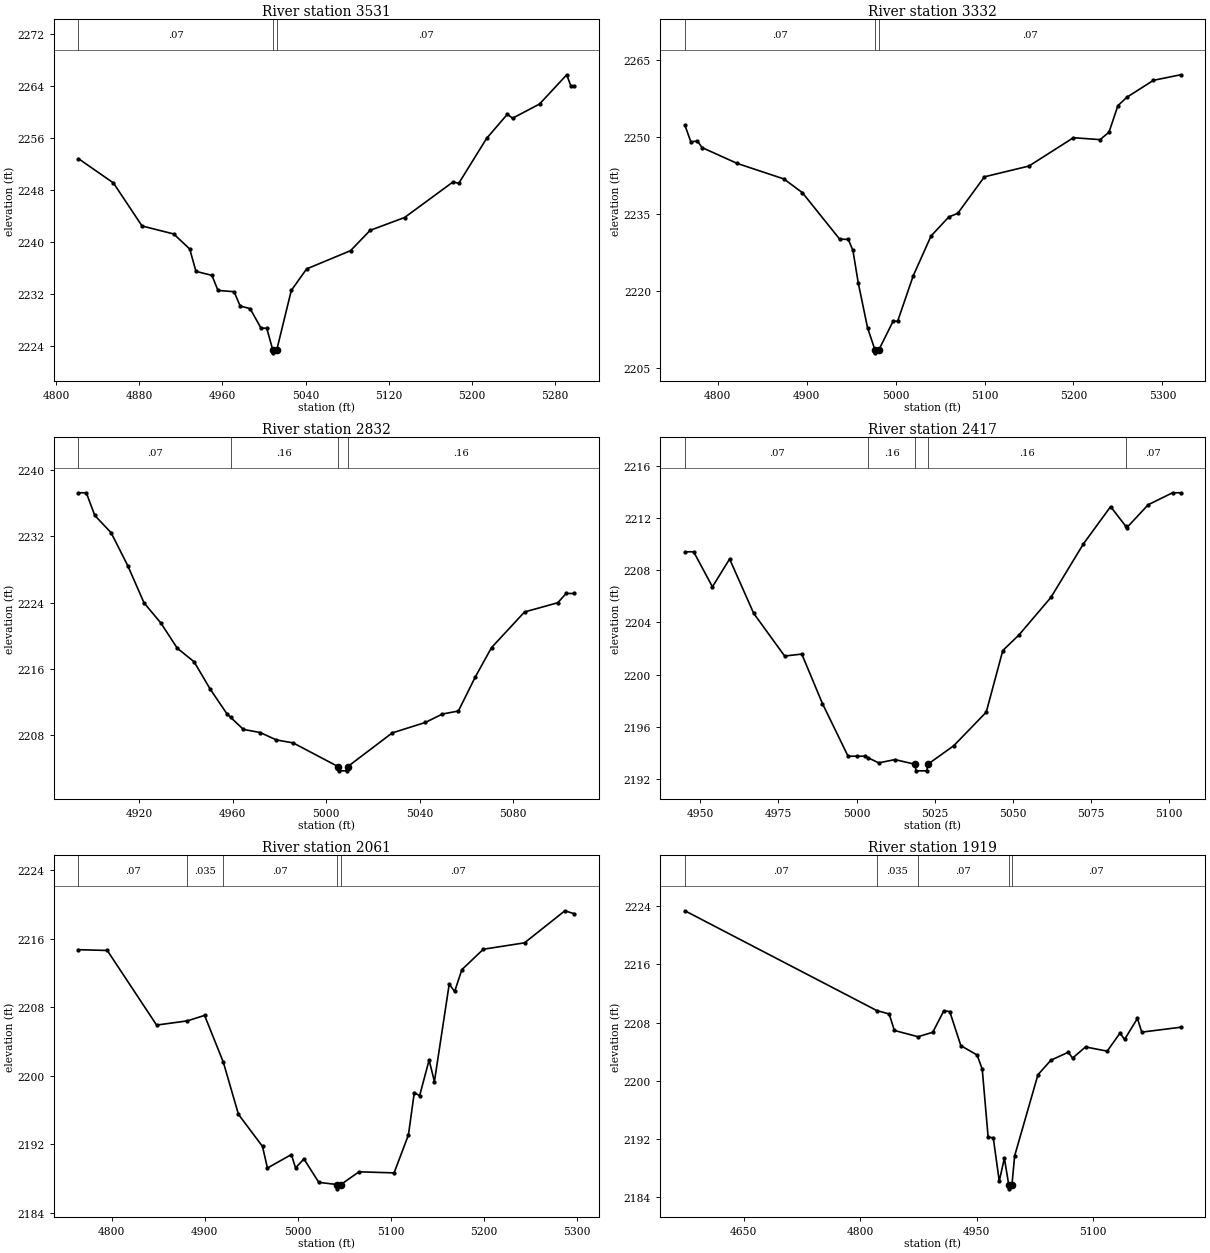
Type RM Length L Ch R = 1 ,3531    ,199,199,199
BEGIN DESCRIPTION:
Sweetwater Creek Trib 15 4481
END DESCRIPTION:
XS GIS Cut Line= 3
       1367622.9      6834751.62      1367774.95      6834658.12
      1367831.23      6834365.38
#Sta/Elev= 30
  4821.5  2252.8  4855.2 2249.06  4882.7 2242.45  4913.2 2241.22  4928.6  2238.9
  4934.5 2235.48  4949.9 2234.86  4955.7 2232.55  4971.2 2232.35    4977 2230.16
  4986.6 2229.75  4997.1 2226.75  5002.6 2226.75  5008.3 2223.46  5008.6 2222.96
  5012.3 2223.46  5026.2 2232.55  5040.9 2235.85  5083.2 2238.66    5102 2241.78
  5135.1 2243.75    5182 2249.25  5187.1 2248.98    5214 2255.91  5233.9 2259.61
    5239 2259.01  5264.9 2261.19    5291 2265.68  5294.9 2263.99  5298.1 2263.99
#Mann= 3 ,-1 , 0
  4821.5     .07       0  5008.3     .07       0  5012.3     .07       0
Bank Sta=5008.3,5012.3
XS Rating Curve= 0 ,0
Exp/Cntr=0.3,0.1

Type RM Length L Ch R = 1 ,3332    ,500,500,500
BEGIN DESCRIPTION:
Sweetwater Creek Trib 15 6.0
END DESCRIPTION:
XS GIS Cut Line= 3
      1367895.26      6834914.35      1367964.13      6834687.89
      1367965.78       6834367.5
#Sta/Elev= 30
  4763.3 2252.26  4769.9 2249.05  4777.4 2249.17  4782.6 2247.91  4822.2 2244.82
  4874.5 2241.82  4895.4 2239.13  4937.2 2230.11  4946.9 2230.06  4952.1 2227.93
  4958.1  2221.6  4968.5 2212.91    4977  2208.5  4977.2    2208    4981  2208.5
  4997.3 2214.16  5002.4 2214.16  5019.9 2222.99  5039.9 2230.72  5059.9 2234.43
  5069.9 2235.12  5099.9 2242.23  5149.9 2244.32  5199.9 2249.83  5229.9 2249.46
  5239.9 2250.91  5249.9 2256.06  5259.9 2257.69  5289.9    2261  5320.4 2262.07
#Mann= 3 ,-1 , 0
  4763.3     .07       0    4977     .07       0    4981     .07       0
Bank Sta=4977,4981
XS Rating Curve= 0 ,0
Exp/Cntr=0.3,0.1

Type RM Length L Ch R = 1 ,2832    ,415,415,415
BEGIN DESCRIPTION:
Sweetwater Creek Trib 15 5.0
END DESCRIPTION:
XS GIS Cut Line= 3
      1368305.03      6834987.97      1368378.31      6834911.38
      1368454.97      6834838.03
#Sta/Elev= 30
    4894 2237.24  4897.4 2237.24    4901 2234.51    4908 2232.42  4915.2  2228.4
  4922.1 2223.95  4929.3 2221.52  4936.3 2218.49  4943.5 2216.85  4950.4 2213.55
  4957.6 2210.55  4959.1 2210.15  4964.6 2208.69  4971.8 2208.31  4978.7 2207.42
  4985.9 2207.06  5005.2 2204.19  5005.5 2203.69    5009 2203.69  5009.2 2204.19
  5028.3 2208.27  5042.5 2209.53  5049.7 2210.54  5056.6 2210.91  5063.8 2215.01
  5070.8 2218.57  5084.9 2222.86  5099.1 2223.97  5102.7 2225.09  5106.1 2225.09
#Mann= 4 ,-1 , 0
    4894     .07       0  4959.1     .16       0  5005.2     .07       0
  5009.2     .16       0
Bank Sta=5005.2,5009.2
XS Rating Curve= 0 ,0
Exp/Cntr=0.3,0.1

Type RM Length L Ch R = 1 ,2417    ,356,356,356
BEGIN DESCRIPTION:
Sweetwater Creek Trib 15 4.0
END DESCRIPTION:
XS GIS Cut Line= 3
      1368604.96      6835188.02      1368654.96      6835165.36
      1368754.99        6835138.
#Sta/Elev= 30
  4945.1  2209.4  4947.9  2209.4  4953.9 2206.72  4959.4 2208.85  4967.1 2204.69
    4977 2201.42  4982.5 2201.57  4989.1 2197.78  4997.3 2193.75    5000 2193.75
  5002.6 2193.75  5003.7 2193.63  5007.1 2193.24  5012.3 2193.49  5018.8 2193.13
    5019 2192.63  5022.5 2192.63  5022.8 2193.13  5031.1 2194.55  5041.5 2197.12
  5046.8 2201.84    5052 2203.04  5062.2 2205.91  5072.6 2210.01  5081.3 2212.86
  5086.2 2211.34  5086.5 2211.25  5093.3    2213  5101.1 2213.92  5103.7 2213.92
#Mann= 5 ,-1 , 0
  4945.1     .07       0  5003.7     .16       0  5018.8     .07       0
  5022.8     .16       0  5086.2     .07       0
Bank Sta=5018.8,5022.8
XS Rating Curve= 0 ,0
Exp/Cntr=0.3,0.1

Type RM Length L Ch R = 1 ,2061    ,142,142,142
BEGIN DESCRIPTION:
Sweetwater Creek Trib 15 3566
END DESCRIPTION:
XS GIS Cut Line= 3
      1368705.68      6835438.84      1368928.36      6835361.27
      1369074.07      6835103.05
#Sta/Elev= 30
  4764.2 2214.72  4795.2 2214.63  4848.2 2205.92  4881.1 2206.41  4899.7 2207.05
  4919.8  2201.6  4936.1  2195.5  4961.9 2191.76  4967.2 2189.24  4992.9 2190.81
  4997.4 2189.25  5006.4  2190.3  5022.3 2187.57    5042 2187.31  5042.2 2186.81
    5046 2187.31  5065.6  2188.8  5103.2 2188.67  5118.6  2193.1  5124.9 2198.05
  5130.6 2197.67  5140.8 2201.84  5146.5 2199.33  5162.4  2210.7  5168.2 2209.84
    5176 2212.39    5199 2214.77  5243.3 2215.52  5286.6 2219.26  5296.5 2218.92
#Mann= 5 ,-1 , 0
  4764.2     .07       0  4881.1    .035       0  4919.8     .07       0
    5042     .07       0    5046     .07       0
Bank Sta=5042,5046
XS Rating Curve= 0 ,0
Exp/Cntr=0.3,0.1

Type RM Length L Ch R = 1 ,1919    ,425,425,425
BEGIN DESCRIPTION:
Sweetwater Creek Trib 15 3.0
END DESCRIPTION:
XS GIS Cut Line= 3
        1368705.        6835738.      1369028.31      6835461.38
       1369124.4      6835271.96
#Sta/Elev= 30
  4574.5 2223.33  4821.4 2209.64  4837.4 2209.17    4844 2206.91  4874.5 2206.05
  4893.4 2206.66  4907.7 2209.61  4915.3  2209.5  4929.6 2204.82  4950.5 2203.54
  4957.1  2201.6  4964.7 2192.27  4971.3 2192.19    4979 2186.24  4985.6 2189.38
  4991.3 2185.68  4991.5 2185.18  4995.3 2185.68  4998.8  2189.7  5028.8 2200.84
  5045.5 2202.83  5067.8 2203.92  5073.4 2203.12    5090 2204.65  5117.9 2204.07
  5134.5 2206.56  5140.2 2205.67  5156.8 2208.56  5162.4 2206.68  5212.4 2207.35
#Mann= 5 ,-1 , 0
  4574.5     .07       0  4821.4    .035       0  4874.5     .07       0
  4991.3     .07       0  4995.3     .07       0
Bank Sta=4991.3,4995.3
XS Rating Curve= 0 ,0
Exp/Cntr=0.3,0.1

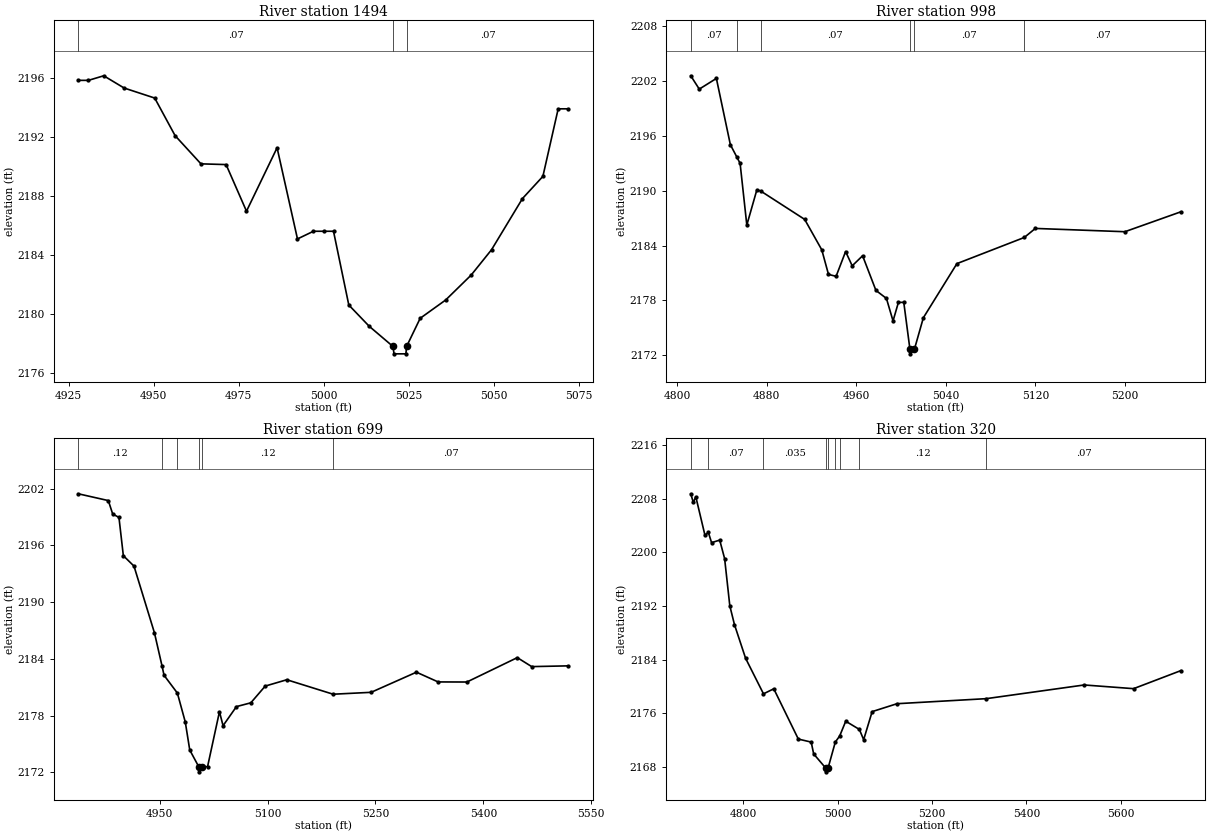
Type RM Length L Ch R = 1 ,1494    ,496,496,496
BEGIN DESCRIPTION:
Sweetwater Creek Trib 15 2.0
END DESCRIPTION:
XS GIS Cut Line= 3
      1369305.02      6835737.98      1369365.05      6835697.87
      1369405.01      6835637.98
#Sta/Elev= 28
  4927.8 2195.84  4930.8 2195.84  4935.3 2196.15  4941.3 2195.32  4950.3 2194.64
  4956.3 2192.09  4963.9 2190.18  4971.3 2190.13  4977.3 2186.97  4986.3 2191.27
  4992.3 2185.09    4997 2185.61    5000 2185.61  5002.9 2185.61  5007.4 2180.61
  5013.4 2179.17  5020.4  2177.8  5020.7  2177.3  5024.2  2177.3  5024.4  2177.8
  5028.4 2179.71  5035.9 2180.95  5043.4 2182.64  5049.4 2184.36  5058.5 2187.83
  5064.5 2189.33    5069 2193.91    5072 2193.91
#Mann= 3 ,-1 , 0
  4927.8     .07       0  5020.4     .07       0  5024.4     .07       0
Bank Sta=5020.4,5024.4
XS Rating Curve= 0 ,0
Exp/Cntr=0.3,0.1

Type RM Length L Ch R = 1 ,998     ,299,299,299
BEGIN DESCRIPTION:
Sweetwater Creek Trib 15 2914
END DESCRIPTION:
XS GIS Cut Line= 3
      1369605.01        6836038.      1369764.14      6835937.89
        1369755.      6835687.96
#Sta/Elev= 30
    4812 2202.58  4819.6 2201.12  4834.9 2202.29  4847.4 2195.04  4853.3 2193.66
  4856.1    2193  4862.1 2186.25  4871.1 2190.11  4874.4 2189.98  4913.8 2186.87
  4929.1 2183.54  4935.1 2180.85  4941.9 2180.64  4950.4 2183.35  4956.3 2181.79
  4965.6 2182.89  4977.5  2179.1  4986.9 2178.22  4992.8 2175.76  4997.6 2177.79
  5002.4 2177.79  5007.9 2172.66  5008.1 2172.16  5011.9 2172.66  5019.9 2176.11
  5049.9 2182.03  5110.1 2184.89    5120 2185.88    5200 2185.52  5250.1  2187.7
#Mann= 6 ,-1 , 0
    4812     .07       0  4853.3     .12       0  4874.4     .07       0
  5007.9     .07       0  5011.9     .07       0  5110.1     .07       0
Bank Sta=5007.9,5011.9
XS Rating Curve= 0 ,0
Exp/Cntr=0.3,0.1

Type RM Length L Ch R = 1 ,699     ,379,379,379
BEGIN DESCRIPTION:
Sweetwater Creek Trib 15 4479
END DESCRIPTION:
XS GIS Cut Line= 3
      1369838.63       6836199.1      1369971.64      6836104.71
      1369947.12      6835587.09
#Sta/Elev= 30
  4836.9 2201.46  4878.7 2200.74  4884.8 2199.32  4893.5 2198.96  4899.6 2194.91
  4914.4 2193.81  4942.8 2186.76  4953.4 2183.24  4956.2 2182.26  4974.7 2180.38
  4985.7 2177.32  4991.9 2174.36  5004.7 2172.55    5005 2172.05  5008.7 2172.55
  5016.7 2172.61  5033.2 2178.41  5038.2 2176.93  5056.8 2178.95  5076.8 2179.35
  5096.8 2181.12  5126.8 2181.79  5191.2 2180.26    5244 2180.46    5307 2182.59
  5337.1 2181.56  5377.1 2181.55  5447.2 2184.13  5467.2 2183.18  5518.2 2183.26
#Mann= 6 ,-1 , 0
  4836.9     .12       0  4953.4     .07       0  4974.7     .12       0
  5004.7     .07       0  5008.7     .12       0  5191.2     .07       0
Bank Sta=5004.7,5008.7
XS Rating Curve= 0 ,0
Exp/Cntr=0.3,0.1

Type RM Length L Ch R = 1 ,320     ,0,0,0
BEGIN DESCRIPTION:
Sweetwater Creek Trib 15 4480
END DESCRIPTION:
XS GIS Cut Line= 3
       1370138.1      6836656.96       1370225.4      6836357.84
      1370012.55      6835661.97
#Sta/Elev= 30
  4688.4 2208.71  4693.8 2207.42  4699.1 2208.27  4718.6  2202.5  4725.7 2202.97
  4732.5 2201.43  4749.8 2201.81  4760.2 2199.05  4771.2 2192.02  4781.1 2189.21
  4804.7  2184.2  4842.6 2178.91  4864.4 2179.66  4916.5 2172.17  4943.8 2171.72
    4949 2169.96  4975.3 2167.79  4975.5 2167.29  4979.3 2167.79  4994.9 2171.73
  5004.1 2172.62    5017 2174.83  5045.9 2173.61    5055 2172.08    5073 2176.26
  5125.8 2177.44  5314.8 2178.19  5522.7 2180.23  5627.3 2179.68  5727.7 2182.37
#Mann= 9 ,-1 , 0
  4688.4    .035       0  4725.7     .07       0  4842.6    .035       0
  4975.3     .04       0  4979.3     .04       0  4994.9     .07       0
  5004.1    .035       0  5045.9     .12       0  5314.8     .07       0
Bank Sta=4975.3,4979.3
XS Rating Curve= 0 ,0
Exp/Cntr=0.3,0.1

Chan Stop Cuts=-1
Use User Specified Reach Order=0
Composite Channel Slope=5