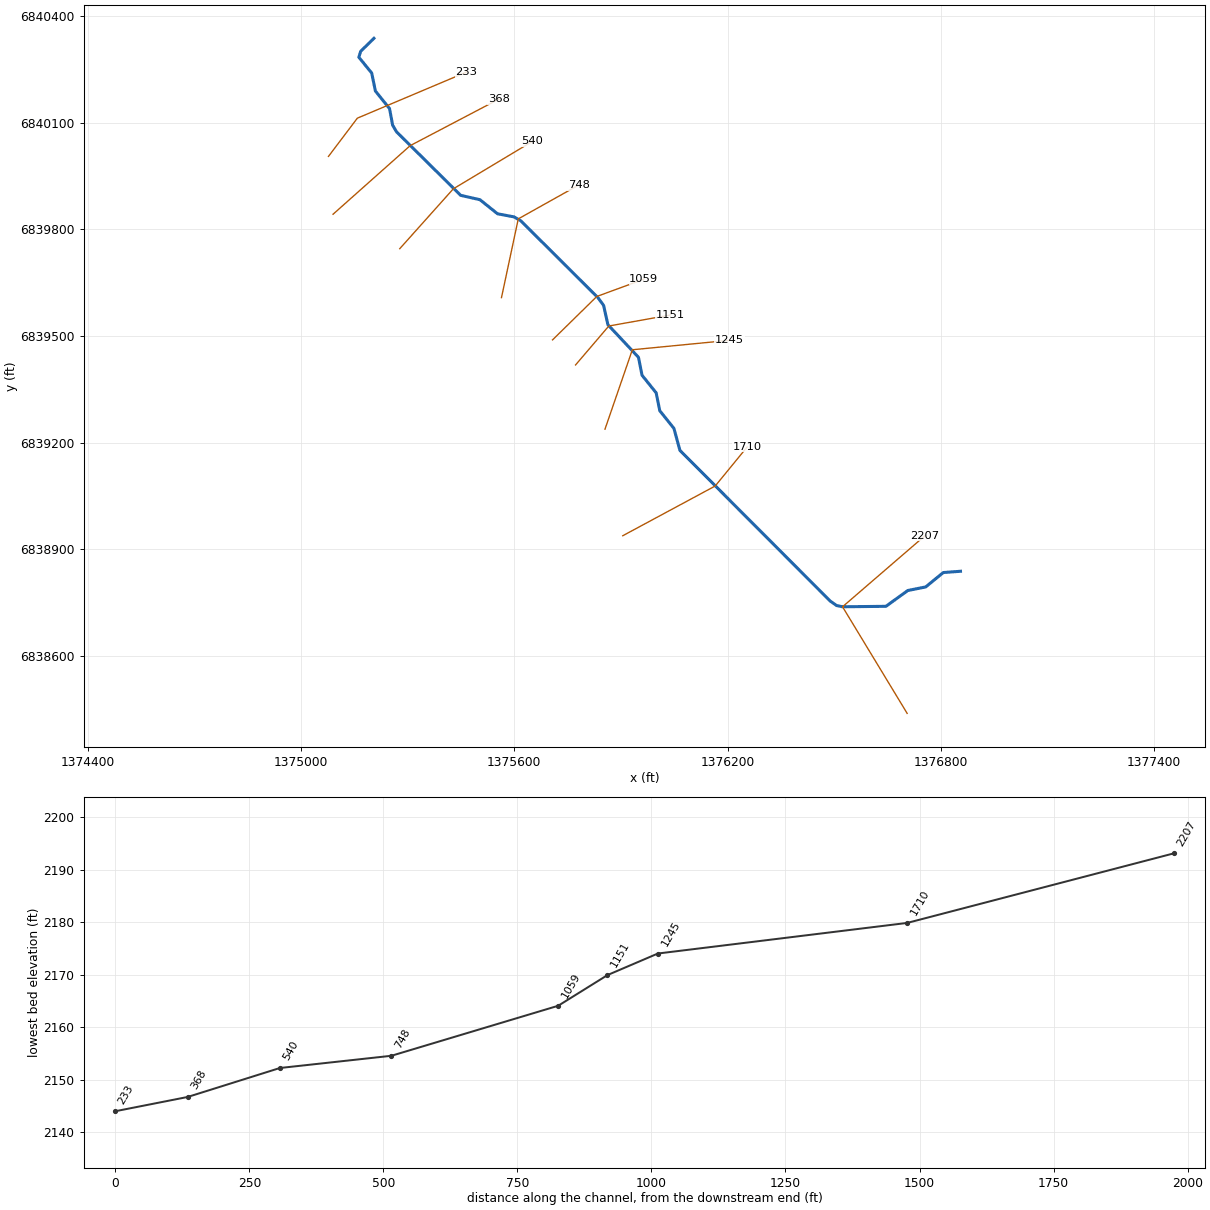
--- Sweetwater Creek Trib 16.prj (project) ---

Proj Title=Sweetwater Creek Trib 16 Base Level Engineering
Current Plan=p01
Default Exp/Contr=0.3,0.1
English Units
Geom File=g01
Flow File=f01
Plan File=p01
BEGIN DESCRIPTION:
Sweetwater Creek Trib 16
END DESCRIPTION:

--- Sweetwater Creek Trib 16.p01 (plan) ---

Plan Title=Multiple Run
Short Identifier=Multiple
Geom File=g01
Flow File=f01
Subcritical Flow
K Sum by GR= 0
Std Step Tol= 0.01
Critical Tol= 0.01
Num of Std Step Trials= 20
Max Error Tol= 0.3
Flow Tol Ratio= 0.001
Split Flow NTrial= 30
Split Flow Tol= 0.02
Split Flow Ratio= 0.02
Log Output Level= 0
Friction Slope Method= 1
Unsteady Friction Slope Method= 2
Unsteady Bridges Friction Slope Method= 1
Parabolic Critical Depth
Global Vel Dist=  1 , 1 , 1
Global Log Level= 0
CheckData=True
Encroach Param= -1, 0, 0, 0
BEGIN DESCRIPTION:
Multiple Run
END DESCRIPTION:

--- Sweetwater Creek Trib 16.f01 (steady flow) ---

Flow Title=Multiple
Number of Profiles=7
Profile Names=10-year,25-year,50-year,1pct_min,100-year,1pct_plu,500-year
River Rch & RM= Sweetwater Creek,Reach-1,2207
     101     136     164      99     198     395     290
Boundary for River Rch & Prof#=Sweetwater Creek,Reach-1,1
Up Type=0
Dn Type=3
Dn Slope=0.005
Boundary for River Rch & Prof#=Sweetwater Creek,Reach-1,2
Up Type=0
Dn Type=3
Dn Slope=0.005
Boundary for River Rch & Prof#=Sweetwater Creek,Reach-1,3
Up Type=0
Dn Type=3
Dn Slope=0.005
Boundary for River Rch & Prof#=Sweetwater Creek,Reach-1,4
Up Type=0
Dn Type=3
Dn Slope=0.005
Boundary for River Rch & Prof#=Sweetwater Creek,Reach-1,5
Up Type=0
Dn Type=3
Dn Slope=0.005
Boundary for River Rch & Prof#=Sweetwater Creek,Reach-1,6
Up Type=0
Dn Type=3
Dn Slope=0.005
Boundary for River Rch & Prof#=Sweetwater Creek,Reach-1,7
Up Type=0
Dn Type=3
Dn Slope=0.005

--- Sweetwater Creek Trib 16.g01 (geometry) ---

Geom Title=Existing Conditions

River Reach=Sweetwater Creek,Reach-1
Reach XY= 30
      1376855.00      6838838.00      1376806.49      6838834.40
      1376757.25      6838793.95      1376706.73      6838783.83
      1376645.34      6838739.35      1376523.23      6838738.07
      1376506.47      6838741.53      1376488.24      6838754.43
      1376065.76      6839178.32      1376048.90      6839240.19
      1376009.16      6839289.72      1375998.92      6839340.20
      1375959.19      6839389.74      1375949.15      6839440.29
      1375863.18      6839531.96      1375851.03      6839586.35
      1375835.21      6839608.09      1375618.21      6839824.38
      1375598.96      6839835.50      1375552.81      6839844.10
      1375503.26      6839883.81      1375448.94      6839896.14
      1375268.62      6840074.79      1375257.61      6840093.63
      1375248.89      6840140.19      1375209.12      6840189.73
      1375198.73      6840240.32      1375162.58      6840284.80
      1375167.67      6840301.40      1375205.00      6840338.00

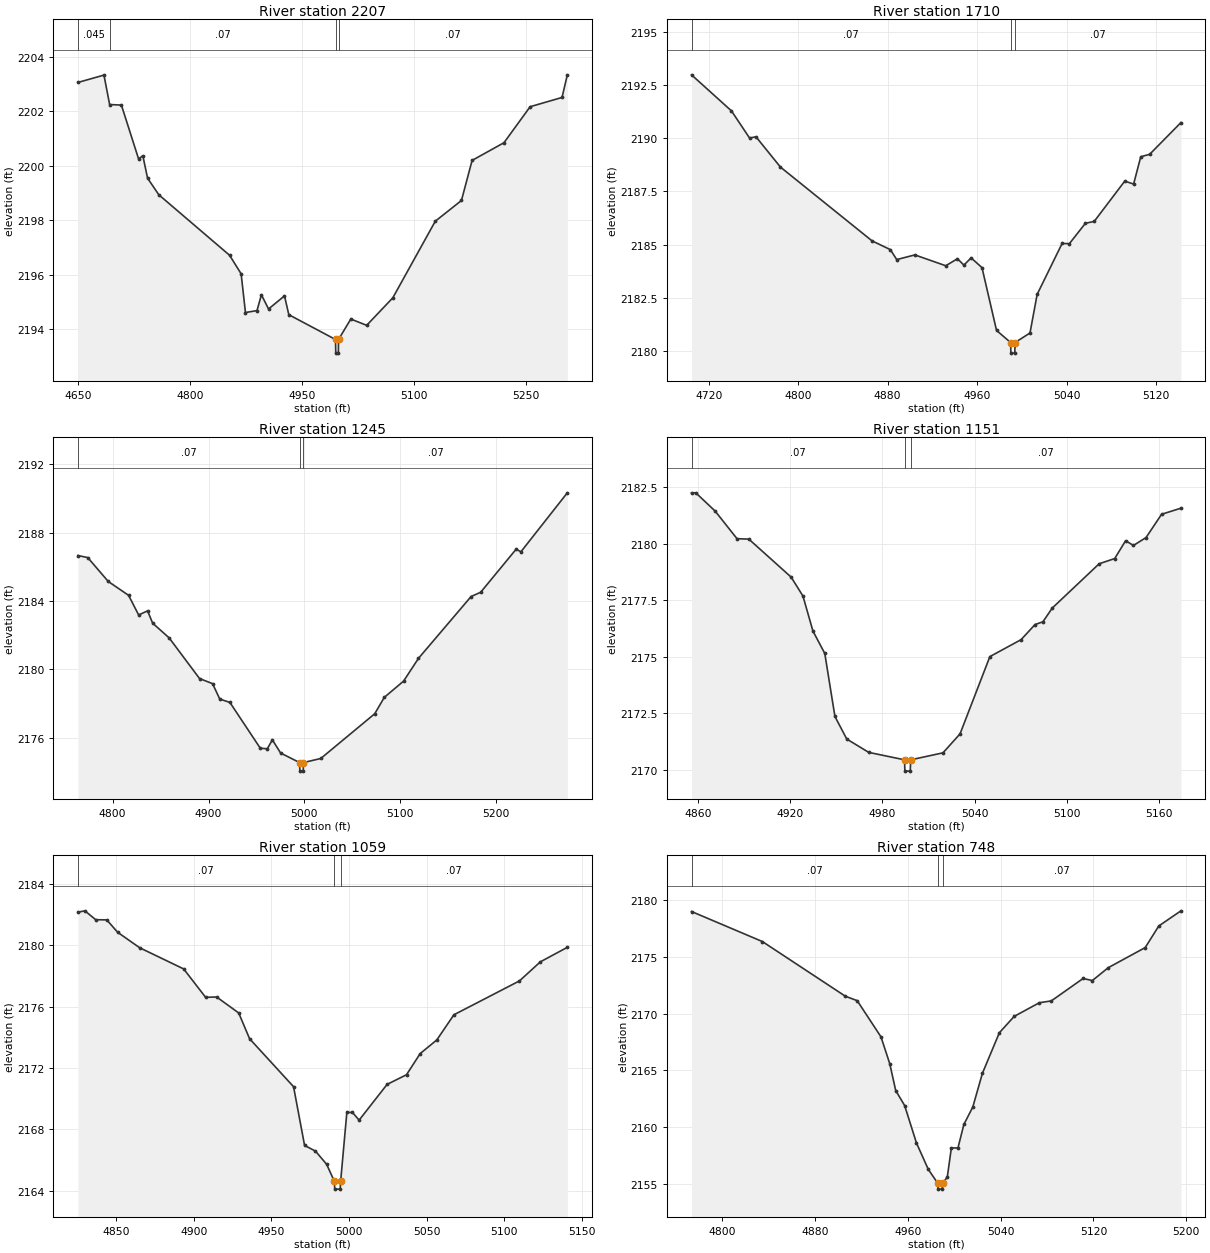
Type RM Length L Ch R = 1,2207,497,497,497
BEGIN DESCRIPTION:
Sweetwater Creek Trib 16 3.0
END DESCRIPTION:
XS GIS Cut Line= 3
      1376704.98      6838438.03      1376523.23      6838738.07
      1376755.01      6838938.01
#Sta/Elev= 30
  4649.2 2203.06  4684.2 2203.33  4691.8 2202.25  4707.6 2202.23  4730.6 2200.26
  4736.4 2200.37  4742.7 2199.55  4757.8 2198.94  4852.8 2196.72  4868.3 2196.04
  4874.1 2194.62  4889.6 2194.69  4895.5 2195.27  4905.1 2194.75  4926.5 2195.23
  4932.3 2194.54  4995.0 2193.63  4995.3 2193.13  4998.8 2193.13  4999.0 2193.63
  5015.5 2194.38  5036.8 2194.15  5071.9 2195.16  5128.9 2197.97  5164.0 2198.73
  5178.3 2200.20  5221.1 2200.85  5256.2 2202.17  5299.0 2202.51  5306.1 2203.34
#Mann=4,-1,0
  4649.2   0.045       0  4691.8    0.07       0  4995.0    0.07       0
  4999.0    0.07       0
Bank Sta=4995,4999
Exp/Cntr=0.3,0.1

Type RM Length L Ch R = 1,1710,465,465,465
BEGIN DESCRIPTION:
Sweetwater Creek Trib 16 2.0
END DESCRIPTION:
XS GIS Cut Line= 3
      1375904.99      6838938.00      1376164.99      6839078.00
      1376254.98      6839187.98
#Sta/Elev= 30
  4704.7 2193.00  4740.4 2191.30  4756.6 2190.02  4762.3 2190.08  4784.2 2188.65
  4866.1 2185.17  4882.4 2184.76  4888.1 2184.29  4904.3 2184.51  4931.9 2184.00
  4942.4 2184.33  4948.1 2184.03  4954.6 2184.37  4964.3 2183.91  4977.3 2180.95
  4989.9 2180.38  4990.1 2179.88  4993.6 2179.88  4993.9 2180.38  5007.2 2180.83
  5013.6 2182.65  5035.9 2185.05  5042.4 2185.04  5056.7 2186.00  5064.6 2186.09
  5091.9 2187.99  5099.8 2187.85  5106.2 2189.14  5114.1 2189.25  5142.1 2190.75
#Mann=3,-1,0
  4704.7    0.07       0  4989.9    0.07       0  4993.9    0.07       0
Bank Sta=4989.9,4993.9
Exp/Cntr=0.3,0.1

Type RM Length L Ch R = 1,1245,94,94,94
BEGIN DESCRIPTION:
Sweetwater Creek Trib 16 1.0
END DESCRIPTION:
XS GIS Cut Line= 3
      1375855.01      6839238.02      1375931.94      6839461.45
      1376204.95      6839488.00
#Sta/Elev= 30
  4763.7 2186.67  4774.0 2186.55  4795.4 2185.15  4816.6 2184.34  4827.1 2183.19
  4836.4 2183.43  4841.7 2182.71  4858.9 2181.85  4890.6 2179.47  4904.2 2179.17
  4911.7 2178.27  4922.3 2178.07  4954.0 2175.39  4961.3 2175.36  4966.6 2175.88
  4975.2 2175.11  4995.0 2174.55  4995.3 2174.05  4998.8 2174.05  4999.0 2174.55
  5017.1 2174.79  5073.4 2177.41  5083.4 2178.37  5103.5 2179.32  5119.0 2180.65
  5173.9 2184.27  5183.9 2184.52  5220.9 2187.04  5225.9 2186.89  5274.3 2190.34
#Mann=3,-1,0
  4763.7    0.07       0  4995.0    0.07       0  4999.0    0.07       0
Bank Sta=4995,4999
Exp/Cntr=0.3,0.1

Type RM Length L Ch R = 1,1151,92,92,92
BEGIN DESCRIPTION:
Sweetwater Creek Trib 16 4128
END DESCRIPTION:
XS GIS Cut Line= 3
      1375772.21      6839418.76      1375865.80      6839528.33
      1376037.39      6839558.98
#Sta/Elev= 30
  4855.9 2182.26  4858.7 2182.26  4871.3 2181.45  4885.5 2180.23  4893.2 2180.21
  4920.7 2178.53  4928.4 2177.69  4934.9 2176.14  4942.6 2175.15  4949.2 2172.36
  4956.9 2171.36  4971.2 2170.77  4994.5 2170.44  4994.7 2169.94  4998.2 2169.94
  4998.5 2170.44  5019.5 2170.75  5030.6 2171.59  5050.0 2175.01  5070.3 2175.76
  5079.4 2176.43  5084.5 2176.55  5090.6 2177.16  5121.1 2179.12  5131.2 2179.35
  5138.3 2180.14  5143.4 2179.93  5151.6 2180.28  5161.7 2181.31  5174.3 2181.58
#Mann=3,-1,0
  4855.9    0.07       0  4994.5    0.07       0  4998.5    0.07       0
Bank Sta=4994.5,4998.5
Exp/Cntr=0.3,0.1

Type RM Length L Ch R = 1,1059,311,311,311
BEGIN DESCRIPTION:
Sweetwater Creek Trib 16 4127
END DESCRIPTION:
XS GIS Cut Line= 3
      1375707.43      6839489.25      1375831.99      6839611.47
      1375963.89      6839659.87
#Sta/Elev= 30
  4825.5 2182.15  4830.0 2182.24  4837.0 2181.66  4844.1 2181.65  4851.1 2180.84
  4865.3 2179.83  4893.6 2178.45  4907.7 2176.60  4914.8 2176.62  4929.0 2175.58
  4936.0 2173.90  4964.3 2170.77  4971.4 2166.94  4978.4 2166.57  4985.6 2165.71
  4990.6 2164.59  4990.8 2164.09  4994.3 2164.09  4994.6 2164.59  4998.6 2169.09
  5002.2 2169.09  5006.5 2168.59  5024.5 2170.92  5037.0 2171.55  5045.8 2172.93
  5056.5 2173.82  5067.5 2175.46  5109.7 2177.67  5123.1 2178.91  5140.5 2179.86
#Mann=3,-1,0
  4825.5    0.07       0  4990.6    0.07       0  4994.6    0.07       0
Bank Sta=4990.6,4994.6
Exp/Cntr=0.3,0.1

Type RM Length L Ch R = 1,748,208,208,208
BEGIN DESCRIPTION:
Sweetwater Creek Trib 16 802
END DESCRIPTION:
XS GIS Cut Line= 3
      1375563.80      6839608.24      1375611.06      6839829.86
      1375781.64      6839925.37
#Sta/Elev= 30
  4773.4 2178.97  4834.5 2176.33  4906.1 2171.52  4916.3 2171.13  4936.8 2167.95
  4944.4 2165.58  4949.5 2163.23  4957.2 2161.91  4967.4 2158.62  4977.6 2156.30
  4985.9 2155.06  4986.1 2154.56  4989.6 2154.56  4989.9 2155.06  4994.0 2155.62
  4997.5 2158.18  5003.2 2158.18  5008.3 2160.25  5016.0 2161.78  5024.3 2164.75
  5038.9 2168.31  5051.7 2169.75  5073.4 2170.95  5083.7 2171.11  5111.1 2173.08
  5119.1 2172.90  5132.8 2174.03  5164.7 2175.80  5176.4 2177.70  5195.5 2179.03
#Mann=3,-1,0
  4773.4    0.07       0  4985.9    0.07       0  4989.9    0.07       0
Bank Sta=4985.9,4989.9
Exp/Cntr=0.3,0.1

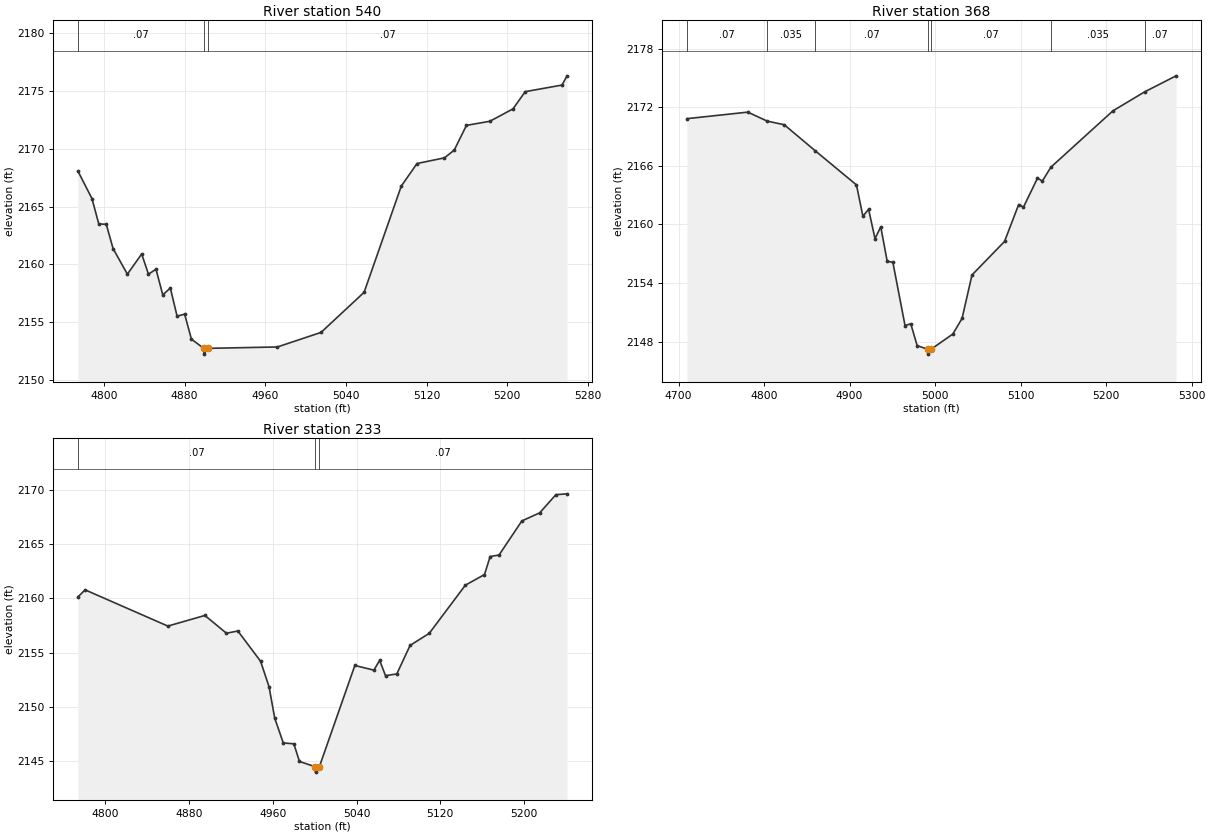
Type RM Length L Ch R = 1,540,172,172,172
BEGIN DESCRIPTION:
Sweetwater Creek Trib 16 4088
END DESCRIPTION:
XS GIS Cut Line= 3
      1375277.69      6839745.95      1375428.18      6839914.29
      1375650.55      6840047.85
#Sta/Elev= 30
  4774.2 2168.08  4788.2 2165.69  4794.9 2163.51  4802.4 2163.46  4809.1 2161.37
  4823.3 2159.15  4837.5 2160.90  4844.2 2159.15  4851.7 2159.58  4858.4 2157.36
  4865.9 2157.95  4872.6 2155.52  4880.1 2155.69  4886.8 2153.53  4899.0 2152.73
  4899.3 2152.23  4903.0 2152.73  4972.1 2152.85  5015.4 2154.11  5058.1 2157.58
  5095.0 2166.78  5110.6 2168.73  5137.8 2169.22  5147.5 2169.89  5159.6 2172.03
  5182.9 2172.39  5205.8 2173.46  5217.9 2174.95  5254.4 2175.52  5259.4 2176.32
#Mann=3,-1,0
  4774.2    0.07       0  4899.0    0.07       0  4903.0    0.07       0
Bank Sta=4899,4903
Exp/Cntr=0.3,0.1

Type RM Length L Ch R = 1,368,135,135,135
BEGIN DESCRIPTION:
Sweetwater Creek Trib 16 4089
END DESCRIPTION:
XS GIS Cut Line= 3
      1375089.99      6839842.88      1375306.84      6840035.89
      1375556.37      6840166.82
#Sta/Elev= 30
  4709.7 2170.84  4780.9 2171.51  4803.6 2170.59  4823.5 2170.22  4859.5 2167.57
  4908.0 2164.05  4915.5 2160.85  4922.2 2161.55  4929.7 2158.54  4936.4 2159.76
  4943.9 2156.24  4950.6 2156.11  4964.8 2149.64  4971.5 2149.82  4979.0 2147.58
  4991.3 2147.21  4991.5 2146.71  4995.3 2147.21  5020.7 2148.77  5031.5 2150.37
  5043.1 2154.82  5081.2 2158.26  5097.7 2162.04  5103.3 2161.77  5119.7 2164.74
  5125.4 2164.45  5135.4 2165.87  5207.9 2171.64  5244.9 2173.58  5281.8 2175.23
#Mann=7,-1,0
  4709.7    0.07       0  4803.6   0.035       0  4859.5    0.07       0
  4991.3    0.07       0  4995.3    0.07       0  5135.4   0.035       0
  5244.9    0.07       0
Bank Sta=4991.3,4995.3
Exp/Cntr=0.3,0.1

Type RM Length L Ch R = 1,233,0,0,0
BEGIN DESCRIPTION:
Sweetwater Creek Trib 16 3907
END DESCRIPTION:
XS GIS Cut Line= 3
      1375077.13      6840005.73      1375158.39      6840113.31
      1375464.84      6840242.78
#Sta/Elev= 30
  4773.6 2160.13  4780.5 2160.79  4859.6 2157.45  4895.0 2158.43  4915.6 2156.79
  4926.5 2157.00  4948.2 2154.21  4956.3 2151.86  4961.7 2148.97  4969.9 2146.68
  4980.0 2146.60  4985.4 2144.97  5000.4 2144.49  5000.7 2143.99  5004.4 2144.49
  5038.3 2153.82  5056.5 2153.39  5062.0 2154.29  5067.6 2152.88  5078.4 2153.04
  5091.1 2155.67  5109.4 2156.78  5143.9 2161.22  5162.2 2162.20  5167.6 2163.86
  5176.1 2164.00  5197.9 2167.14  5215.0 2167.89  5230.4 2169.56  5241.1 2169.64
#Mann=3,-1,0
  4773.6    0.07       0  5000.4    0.07       0  5004.4    0.07       0
Bank Sta=5000.4,5004.4
Exp/Cntr=0.3,0.1

Chan Stop Cuts=-1