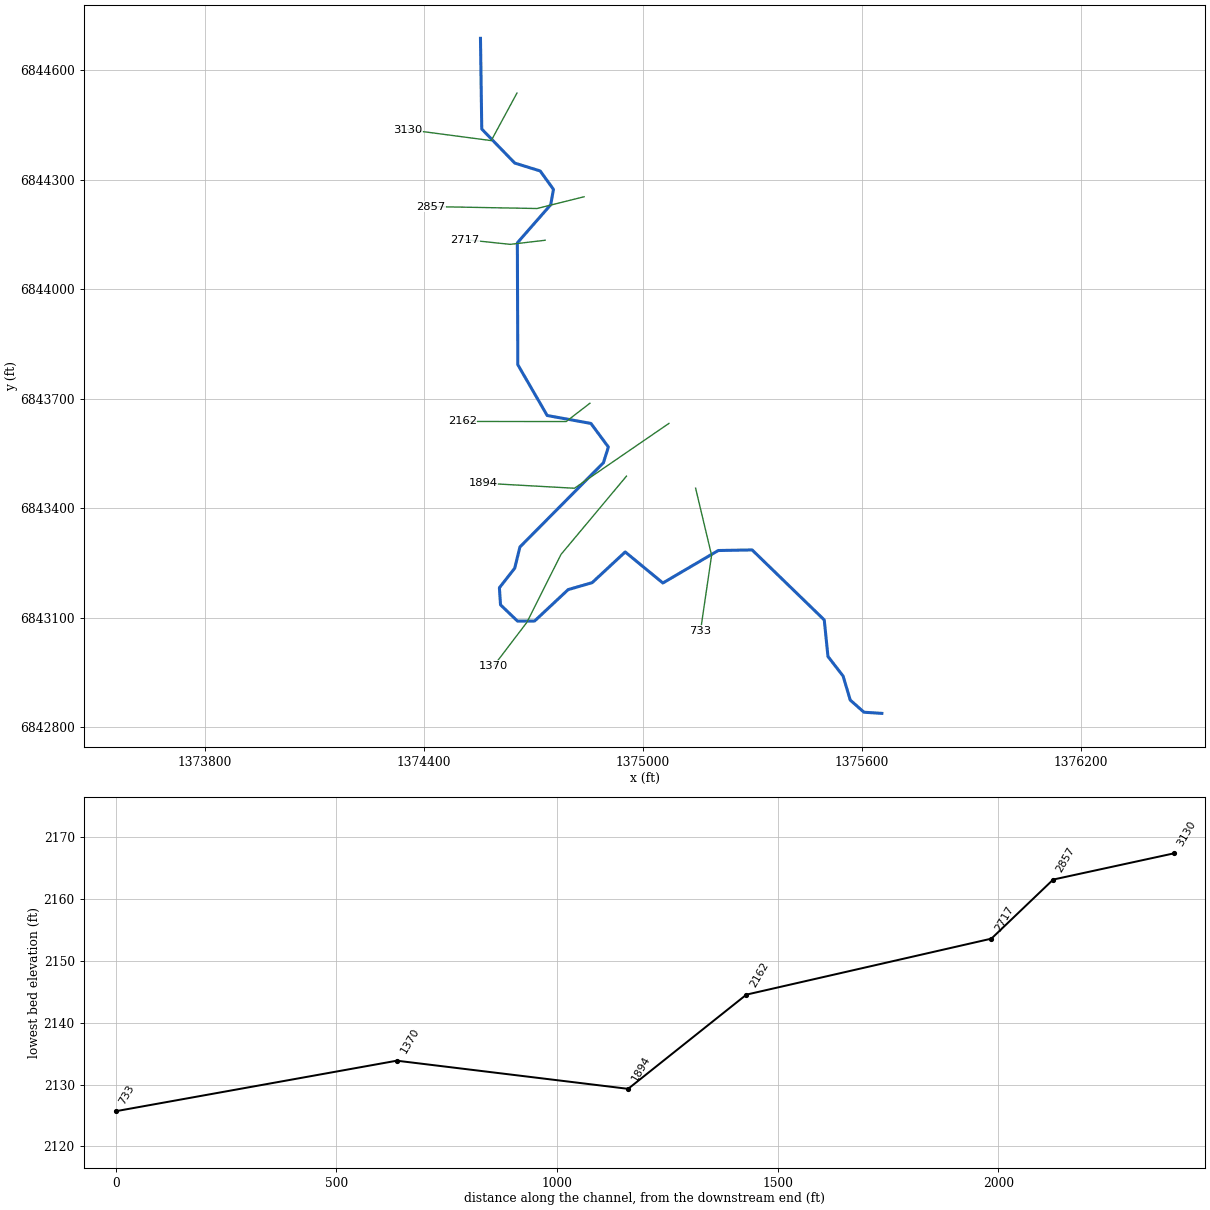
--- Sweetwater Creek Trib 17.prj (project) ---

Proj Title=Sweetwater Creek Trib 17 Base Level Engineering
Current Plan=p01
Default Exp/Contr=0.3,0.1
English Units
Geom File=g01
Flow File=f01
Plan File=p01
BEGIN DESCRIPTION:
Sweetwater Creek Trib 17
END DESCRIPTION:

--- Sweetwater Creek Trib 17.p01 (plan) ---

Plan Title=Multiple Run
Short Identifier=Multiple
Geom File=g01
Flow File=f01
Subcritical Flow
K Sum by GR= 0
Std Step Tol= 0.01
Critical Tol= 0.01
Num of Std Step Trials= 20
Max Error Tol= 0.3
Flow Tol Ratio= 0.001
Split Flow NTrial= 30
Split Flow Tol= 0.02
Split Flow Ratio= 0.02
Log Output Level= 0
Friction Slope Method= 1
Unsteady Friction Slope Method= 2
Unsteady Bridges Friction Slope Method= 1
Parabolic Critical Depth
Global Vel Dist=  1 , 1 , 1
Global Log Level= 0
CheckData=True
Encroach Param= -1, 0, 0, 0
BEGIN DESCRIPTION:
Multiple Run
END DESCRIPTION:

--- Sweetwater Creek Trib 17.f01 (steady flow) ---

Flow Title=Multiple
Number of Profiles=7
Profile Names=10-year,25-year,50-year,1pct_min,100-year,1pct_plu,500-year
River Rch & RM= Sweetwater Creek,Reach-1,3130
     116     156     189     114     228     456     336
Boundary for River Rch & Prof#=Sweetwater Creek,Reach-1,1
Up Type=0
Dn Type=3
Dn Slope=0.005
Boundary for River Rch & Prof#=Sweetwater Creek,Reach-1,2
Up Type=0
Dn Type=3
Dn Slope=0.005
Boundary for River Rch & Prof#=Sweetwater Creek,Reach-1,3
Up Type=0
Dn Type=3
Dn Slope=0.005
Boundary for River Rch & Prof#=Sweetwater Creek,Reach-1,4
Up Type=0
Dn Type=3
Dn Slope=0.005
Boundary for River Rch & Prof#=Sweetwater Creek,Reach-1,5
Up Type=0
Dn Type=3
Dn Slope=0.005
Boundary for River Rch & Prof#=Sweetwater Creek,Reach-1,6
Up Type=0
Dn Type=3
Dn Slope=0.005
Boundary for River Rch & Prof#=Sweetwater Creek,Reach-1,7
Up Type=0
Dn Type=3
Dn Slope=0.005

--- Sweetwater Creek Trib 17.g01 (geometry) ---

Geom Title=Existing Conditions

River Reach=Sweetwater Creek,Reach-1
Reach XY= 30
      1374555.00      6844688.00      1374558.53      6844439.45
      1374648.96      6844346.16      1374718.71      6844324.51
      1374755.02      6844274.07      1374747.53      6844231.98
      1374656.06      6844127.56      1374657.35      6843793.52
      1374737.87      6843654.30      1374857.75      6843632.58
      1374905.52      6843567.95      1374891.90      6843524.80
      1374663.14      6843294.06      1374648.82      6843235.81
      1374606.86      6843182.24      1374609.98      6843135.38
      1374656.37      6843091.01      1374703.31      6843091.09
      1374795.33      6843177.20      1374861.05      6843196.20
      1374951.67      6843280.38      1375054.91      6843195.31
      1375206.59      6843284.33      1375299.52      6843285.92
      1375497.14      6843094.17      1375507.33      6842993.97
      1375548.87      6842940.16      1375568.37      6842874.45
      1375606.03      6842841.14      1375655.00      6842838.00

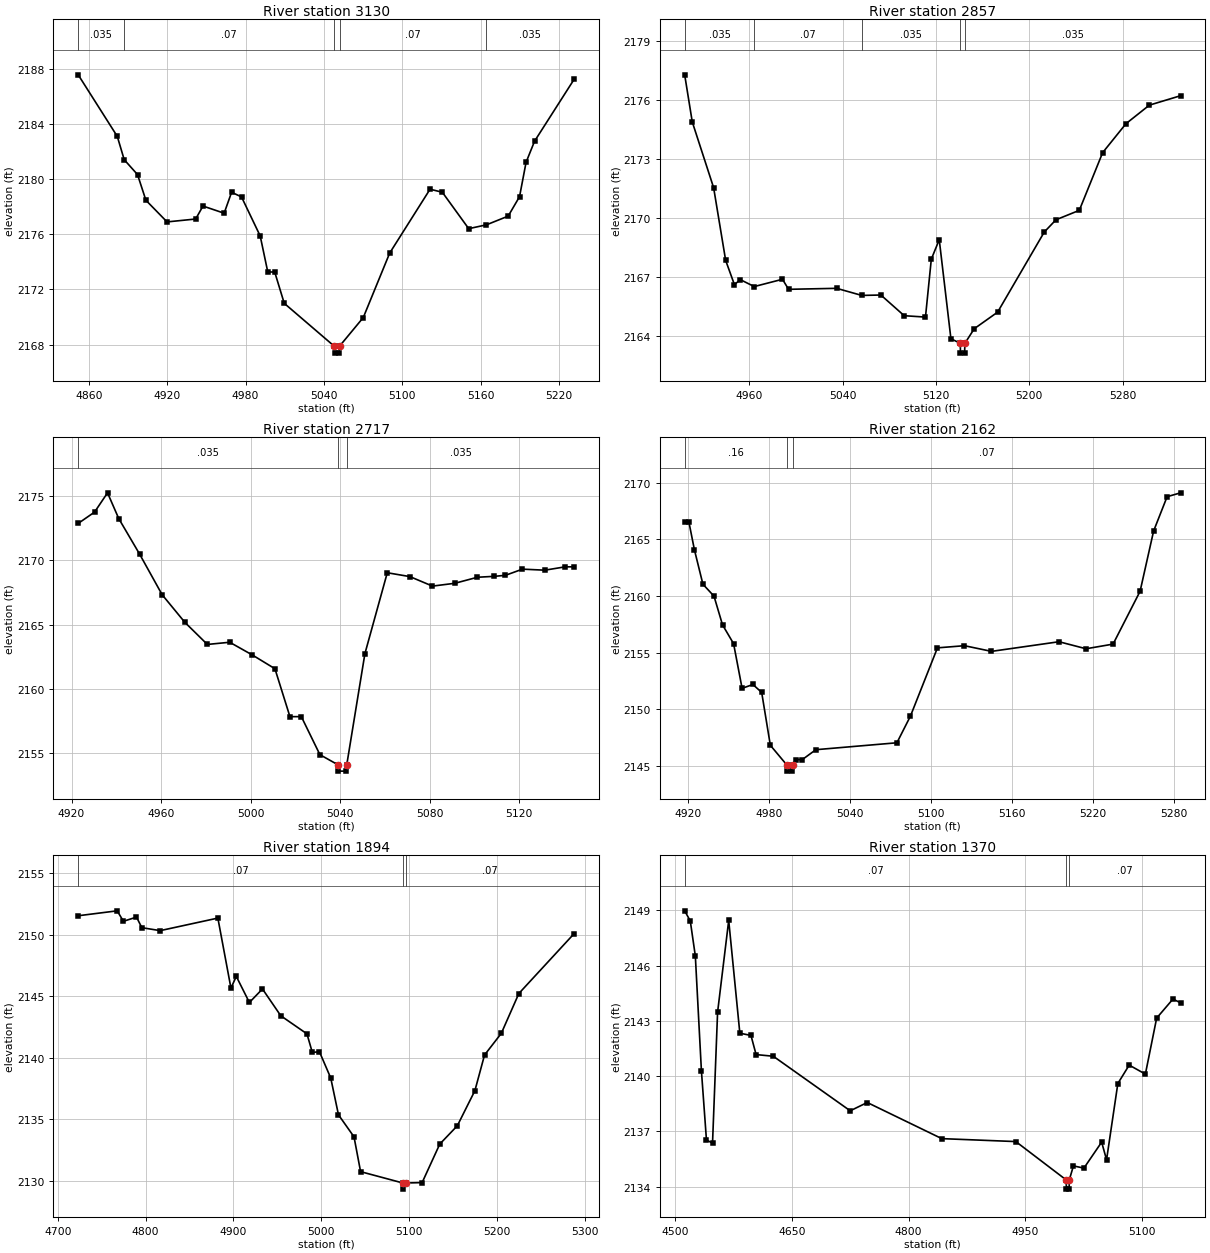
Type RM Length L Ch R = 1,3130,273,273,273
BEGIN DESCRIPTION:
Sweetwater Creek Trib 17 5.0
END DESCRIPTION:
XS GIS Cut Line= 3
      1374654.98      6844537.96      1374584.48      6844407.72
      1374354.97      6844438.00
#Sta/Elev= 30
  4851.9 2187.55  4881.8 2183.09  4887.1 2181.40  4897.3 2180.32  4903.7 2178.46
  4919.9 2176.89  4941.8 2177.10  4947.4 2178.04  4963.6 2177.52  4969.3 2179.04
  4976.9 2178.70  4991.2 2175.87  4997.0 2173.26  5002.3 2173.26  5009.6 2170.99
  5047.9 2167.88  5048.2 2167.38  5051.7 2167.38  5051.9 2167.88  5070.1 2169.96
  5090.3 2174.63  5121.2 2179.26  5130.6 2179.04  5150.8 2176.40  5164.4 2176.68
  5181.0 2177.31  5189.7 2178.72  5194.7 2181.21  5201.2 2182.74  5231.5 2187.23
#Mann=5,-1,0
  4851.9   0.035       0  4887.1    0.07       0  5047.9    0.07       0
  5051.9    0.07       0  5164.4   0.035       0
Bank Sta=5047.9,5051.9
Exp/Cntr=0.3,0.1

Type RM Length L Ch R = 1,2857,140,140,140
BEGIN DESCRIPTION:
Sweetwater Creek Trib 17 4098
END DESCRIPTION:
XS GIS Cut Line= 3
      1374839.08      6844253.88      1374709.95      6844221.60
      1374418.20      6844226.95
#Sta/Elev= 30
  4904.7 2177.28  4911.2 2174.89  4929.5 2171.55  4939.8 2167.86  4947.3 2166.63
  4952.4 2166.88  4964.3 2166.53  4988.5 2166.90  4993.7 2166.39  5034.9 2166.44
  5056.4 2166.08  5072.8 2166.10  5092.8 2165.05  5111.0 2164.98  5116.0 2167.92
  5122.8 2168.91  5132.8 2163.88  5140.8 2163.65  5141.0 2163.15  5144.5 2163.15
  5144.8 2163.65  5152.8 2164.39  5172.8 2165.23  5212.8 2169.30  5222.8 2169.92
  5242.8 2170.40  5262.8 2173.33  5282.8 2174.80  5302.8 2175.74  5329.6 2176.22
#Mann=5,-1,0
  4904.7   0.035       0  4964.3    0.07       0  5056.4   0.035       0
  5140.8    0.07       0  5144.8   0.035       0
Bank Sta=5140.8,5144.8
Exp/Cntr=0.3,0.1

Type RM Length L Ch R = 1,2717,555,555,555
BEGIN DESCRIPTION:
Sweetwater Creek Trib 17 4.0
END DESCRIPTION:
XS GIS Cut Line= 3
      1374732.26      6844134.62      1374636.55      6844123.38
      1374512.00      6844136.48
#Sta/Elev= 30
  4923.0 2172.88  4930.3 2173.76  4936.1 2175.26  4941.1 2173.26  4950.4 2170.50
  4960.5 2167.33  4970.6 2165.19  4980.7 2163.46  4990.7 2163.63  5000.8 2162.64
  5010.9 2161.57  5017.6 2157.84  5022.7 2157.84  5031.0 2154.88  5039.0 2154.10
  5039.3 2153.60  5042.8 2153.60  5043.0 2154.10  5051.1 2162.74  5061.1 2169.04
  5071.2 2168.74  5081.3 2168.00  5091.3 2168.22  5101.4 2168.69  5108.9 2168.76
  5113.9 2168.84  5121.5 2169.32  5131.5 2169.24  5140.6 2169.50  5144.6 2169.50
#Mann=3,-1,0
  4923.0   0.035       0  5039.0   0.035       0  5043.0   0.035       0
Bank Sta=5039,5043
Exp/Cntr=0.3,0.1

Type RM Length L Ch R = 1,2162,268,268,268
BEGIN DESCRIPTION:
Sweetwater Creek Trib 17 3.0
END DESCRIPTION:
XS GIS Cut Line= 3
      1374854.98      6843687.98      1374789.88      6843637.79
      1374504.98      6843638.00
#Sta/Elev= 30
  4917.8 2166.53  4920.9 2166.53  4925.0 2164.07  4931.3 2161.03  4939.5 2159.98
  4945.8 2157.45  4954.0 2155.79  4960.3 2151.85  4968.3 2152.19  4974.8 2151.49
  4981.2 2146.83  4993.7 2145.05  4993.9 2144.55  4997.4 2144.55  4997.7 2145.05
  4999.9 2145.57  5004.9 2145.57  5014.9 2146.44  5074.9 2147.05  5084.9 2149.40
  5104.9 2155.42  5124.9 2155.61  5144.9 2155.11  5194.9 2155.96  5214.9 2155.34
  5234.9 2155.75  5254.9 2160.41  5264.9 2165.72  5274.9 2168.75  5284.9 2169.09
#Mann=3,-1,0
  4917.8    0.16       0  4993.7    0.07       0  4997.7    0.07       0
Bank Sta=4993.7,4997.7
Exp/Cntr=0.3,0.1

Type RM Length L Ch R = 1,1894,524,524,524
BEGIN DESCRIPTION:
Sweetwater Creek Trib 17 2.0
END DESCRIPTION:
XS GIS Cut Line= 3
      1375071.58      6843632.76      1374812.55      6843454.97
      1374562.11      6843468.90
#Sta/Elev= 30
  4723.2 2151.54  4767.6 2151.94  4774.7 2151.09  4789.6 2151.43  4795.7 2150.57
  4816.6 2150.33  4882.3 2151.35  4897.2 2145.66  4903.3 2146.61  4918.2 2144.49
  4933.1 2145.59  4954.0 2143.41  4983.8 2141.94  4989.9 2140.43  4998.0 2140.49
  5010.9 2138.35  5019.7 2135.36  5037.4 2133.57  5044.9 2130.74  5093.0 2129.82
  5093.3 2129.32  5097.0 2129.82  5115.0 2129.85  5135.1 2132.98  5155.1 2134.47
  5175.1 2137.32  5186.1 2140.22  5205.2 2141.98  5225.2 2145.22  5288.2 2150.09
#Mann=3,-1,0
  4723.2    0.07       0  5093.0    0.07       0  5097.0    0.07       0
Bank Sta=5093,5097
Exp/Cntr=0.3,0.1

Type RM Length L Ch R = 1,1370,637,637,637
BEGIN DESCRIPTION:
Sweetwater Creek Trib 17 1.0
END DESCRIPTION:
XS GIS Cut Line= 4
      1374955.01      6843488.01      1374775.65      6843273.54
      1374682.11      6843087.40      1374591.51      6842968.35
#Sta/Elev= 30
  4512.1 2148.97  4519.3 2148.42  4525.8 2146.52  4533.6 2140.30  4540.1 2136.53
  4547.9 2136.37  4554.4 2143.47  4568.7 2148.45  4583.0 2142.33  4597.3 2142.21
  4603.9 2141.17  4626.0 2141.08  4724.9 2138.12  4746.8 2138.57  4842.6 2136.61
  4937.8 2136.45  5002.5 2134.37  5002.8 2133.87  5006.3 2133.87  5006.5 2134.37
  5011.8 2135.13  5025.3 2135.01  5048.1 2136.42  5054.4 2135.46  5068.9 2139.60
  5083.5 2140.60  5104.3 2140.11  5118.8 2143.15  5139.7 2144.18  5149.6 2143.98
#Mann=3,-1,0
  4512.1    0.07       0  5002.5    0.07       0  5006.5    0.07       0
Bank Sta=5002.5,5006.5
Exp/Cntr=0.3,0.1

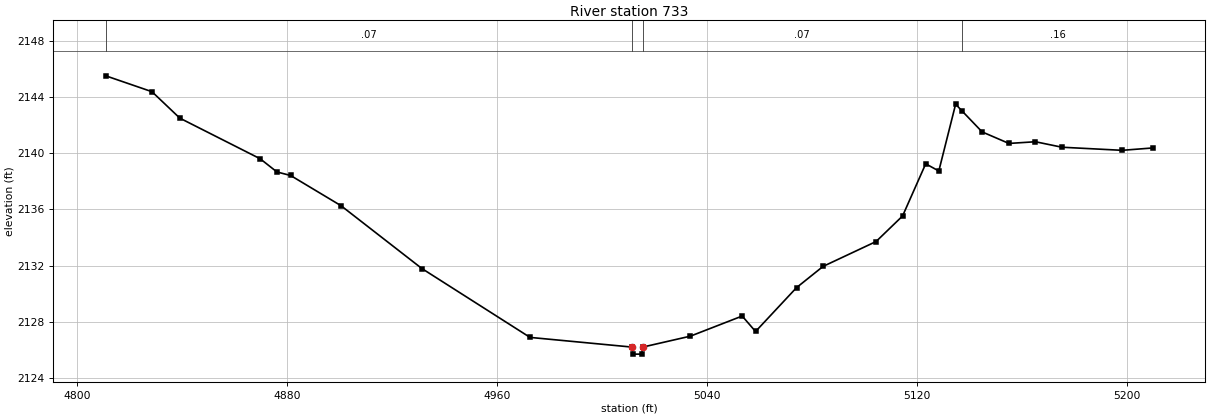
Type RM Length L Ch R = 1,733,0,0,0
BEGIN DESCRIPTION:
Sweetwater Creek Trib 17 638
END DESCRIPTION:
XS GIS Cut Line= 3
      1375144.58      6843455.17      1375188.40      6843271.22
      1375157.96      6843063.64
#Sta/Elev= 30
  4810.9 2145.50  4828.5 2144.37  4839.1 2142.49  4869.7 2139.60  4876.1 2138.66
  4881.3 2138.41  4900.5 2136.26  4931.3 2131.79  4972.5 2126.89  5011.4 2126.20
  5011.6 2125.70  5015.1 2125.70  5015.4 2126.20  5033.6 2126.98  5053.3 2128.41
  5058.4 2127.31  5074.0 2130.43  5084.1 2131.94  5104.3 2133.71  5114.4 2135.53
  5123.2 2139.24  5128.2 2138.73  5134.6 2143.48  5137.0 2143.01  5144.7 2141.51
  5154.9 2140.69  5165.0 2140.81  5175.1 2140.42  5198.0 2140.20  5209.8 2140.37
#Mann=4,-1,0
  4810.9    0.07       0  5011.4    0.07       0  5015.4    0.07       0
  5137.0    0.16       0
Bank Sta=5011.4,5015.4
Exp/Cntr=0.3,0.1

Chan Stop Cuts=-1