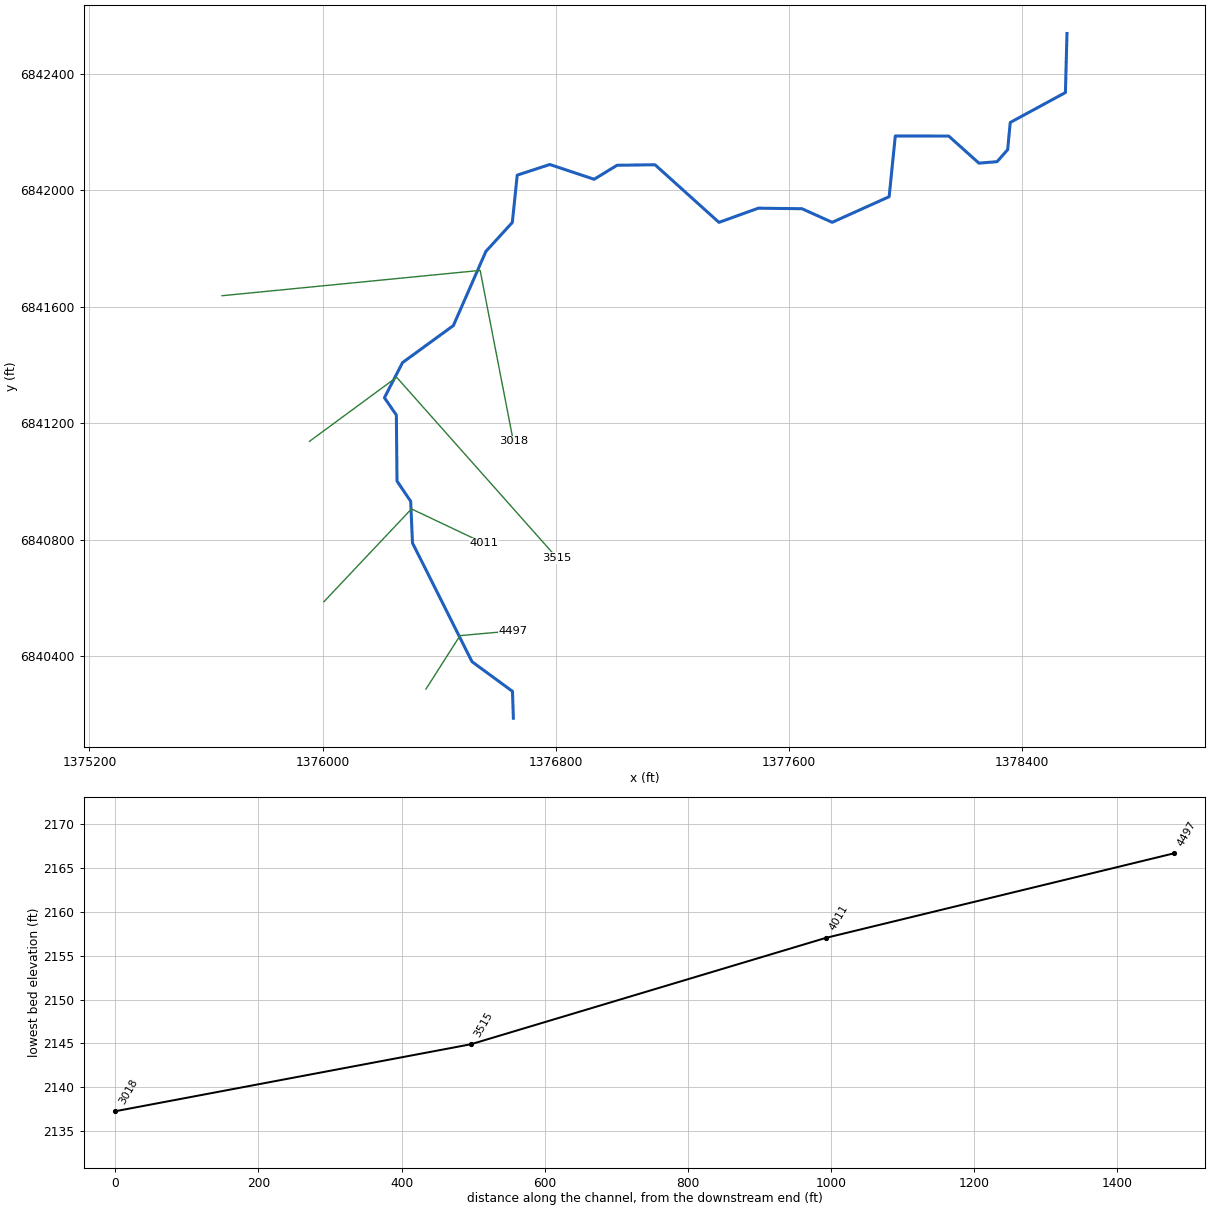
--- Sweetwater Creek Trib 18.prj (project) ---

Proj Title=Sweetwater Creek Trib 18 Base Level Engineering
Current Plan=p01
Default Exp/Contr=0.3,0.1
English Units
Geom File=g01
Flow File=f01
Plan File=p01
BEGIN DESCRIPTION:
Sweetwater Creek Trib 18
END DESCRIPTION:

--- Sweetwater Creek Trib 18.p01 (plan) ---

Plan Title=Multiple Run
Short Identifier=Multiple
Geom File=g01
Flow File=f01
Subcritical Flow
K Sum by GR= 0
Std Step Tol= 0.01
Critical Tol= 0.01
Num of Std Step Trials= 20
Max Error Tol= 0.3
Flow Tol Ratio= 0.001
Split Flow NTrial= 30
Split Flow Tol= 0.02
Split Flow Ratio= 0.02
Log Output Level= 0
Friction Slope Method= 1
Unsteady Friction Slope Method= 2
Unsteady Bridges Friction Slope Method= 1
Parabolic Critical Depth
Global Vel Dist=  1 , 1 , 1
Global Log Level= 0
CheckData=True
Encroach Param= -1, 0, 0, 0
BEGIN DESCRIPTION:
Multiple Run
END DESCRIPTION:

--- Sweetwater Creek Trib 18.f01 (steady flow) ---

Flow Title=Multiple
Number of Profiles=7
Profile Names=10-year,25-year,50-year,1pct_min,100-year,1pct_plu,500-year
River Rch & RM= Sweetwater Creek,Reach-1,4497
      88     116     138      82     164     327     233
Boundary for River Rch & Prof#=Sweetwater Creek,Reach-1,1
Up Type=0
Dn Type=3
Dn Slope=0.005
Boundary for River Rch & Prof#=Sweetwater Creek,Reach-1,2
Up Type=0
Dn Type=3
Dn Slope=0.005
Boundary for River Rch & Prof#=Sweetwater Creek,Reach-1,3
Up Type=0
Dn Type=3
Dn Slope=0.005
Boundary for River Rch & Prof#=Sweetwater Creek,Reach-1,4
Up Type=0
Dn Type=3
Dn Slope=0.005
Boundary for River Rch & Prof#=Sweetwater Creek,Reach-1,5
Up Type=0
Dn Type=3
Dn Slope=0.005
Boundary for River Rch & Prof#=Sweetwater Creek,Reach-1,6
Up Type=0
Dn Type=3
Dn Slope=0.005
Boundary for River Rch & Prof#=Sweetwater Creek,Reach-1,7
Up Type=0
Dn Type=3
Dn Slope=0.005

--- Sweetwater Creek Trib 18.g01 (geometry) ---

Geom Title=Existing Conditions

River Reach=Sweetwater Creek,Reach-1
Reach XY= 30
      1376655.00      6840188.00      1376652.01      6840280.18
      1376513.14      6840381.93      1376308.76      6840789.56
      1376302.61      6840932.47      1376255.68      6841001.92
      1376253.45      6841228.41      1376212.53      6841288.01
      1376274.62      6841408.47      1376449.17      6841535.69
      1376560.85      6841790.29      1376651.45      6841889.47
      1376668.20      6842051.75      1376779.99      6842088.42
      1376932.23      6842037.72      1377010.94      6842085.75
      1377141.14      6842087.48      1377360.62      6841889.73
      1377495.72      6841938.45      1377645.35      6841936.60
      1377749.29      6841889.94      1377944.68      6841977.83
      1377965.79      6842186.30      1378149.14      6842185.93
      1378252.74      6842093.07      1378315.05      6842098.02
      1378351.44      6842139.29      1378360.25      6842232.55
      1378549.65      6842335.30      1378555.00      6842538.00

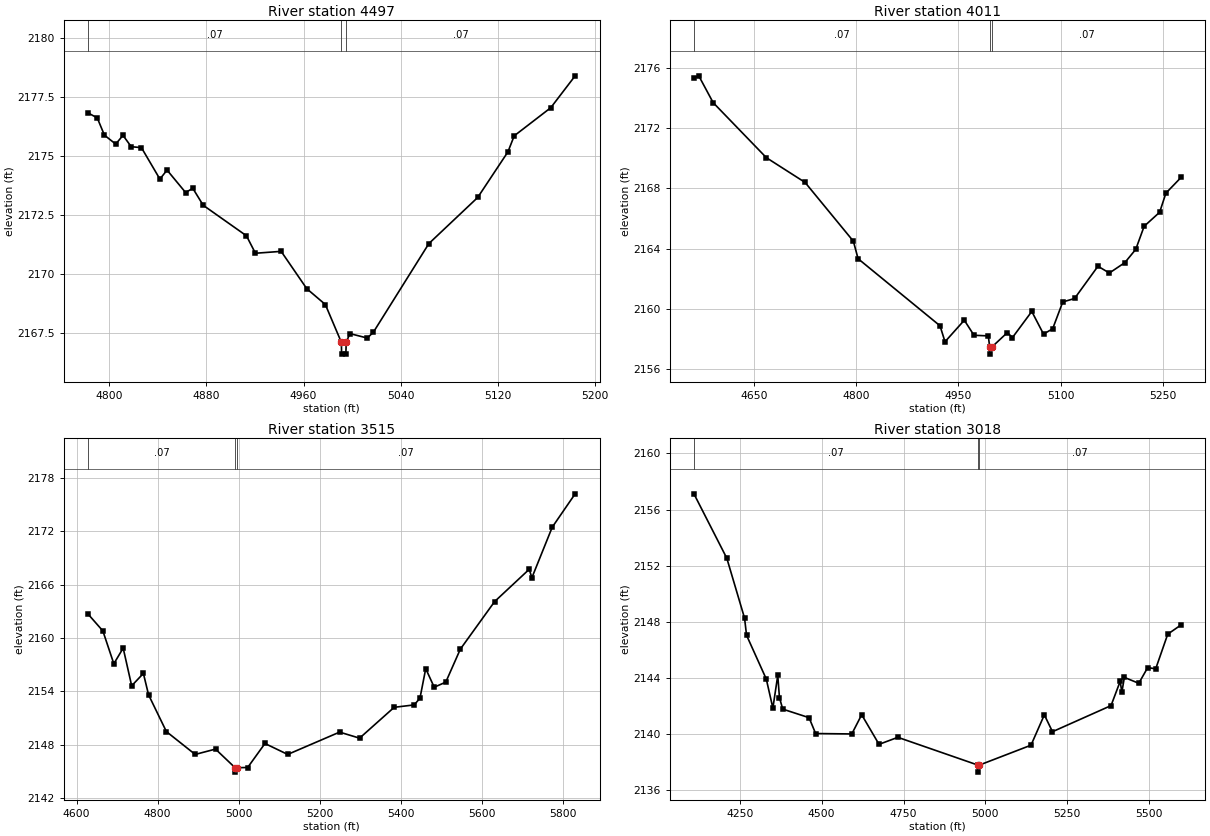
Type RM Length L Ch R = 1,4497,486,486,486
BEGIN DESCRIPTION:
Sweetwater Creek Trib 18 7.0
END DESCRIPTION:
XS GIS Cut Line= 3
      1376355.01      6840288.01      1376472.02      6840471.48
      1376654.97      6840488.00
#Sta/Elev= 30
  4782.4 2176.83  4790.0 2176.62  4795.9 2175.89  4805.2 2175.51  4811.2 2175.88
  4818.0 2175.40  4826.4 2175.36  4841.6 2174.03  4847.5 2174.41  4862.8 2173.46
  4868.7 2173.64  4877.3 2172.92  4912.9 2171.63  4920.3 2170.89  4941.5 2170.97
  4962.6 2169.39  4977.9 2168.72  4991.1 2167.12  4991.3 2166.62  4994.8 2166.62
  4995.1 2167.12  4998.1 2167.49  5012.5 2167.30  5017.5 2167.55  5063.2 2171.30
  5103.4 2173.25  5128.3 2175.18  5133.5 2175.86  5163.6 2177.05  5183.7 2178.40
#Mann=3,-1,0
  4782.4    0.07       0  4991.1    0.07       0  4995.1    0.07       0
Bank Sta=4991.1,4995.1
Exp/Cntr=0.3,0.1

Type RM Length L Ch R = 1,4011,496,496,496
BEGIN DESCRIPTION:
Sweetwater Creek Trib 18 6.0
END DESCRIPTION:
XS GIS Cut Line= 3
      1376004.97      6840587.97      1376305.36      6840906.33
      1376555.03      6840787.99
#Sta/Elev= 30
  4562.3 2175.32  4569.4 2175.47  4590.5 2173.69  4668.5 2170.04  4725.2 2168.40
  4796.0 2164.50  4802.9 2163.34  4923.0 2158.89  4930.3 2157.83  4958.6 2159.26
  4972.8 2158.26  4993.8 2158.22  4995.7 2157.51  4996.0 2157.01  4999.7 2157.51
  5021.7 2158.44  5029.2 2158.11  5057.5 2159.84  5074.7 2158.34  5088.1 2158.69
  5102.9 2160.47  5120.2 2160.70  5154.5 2162.84  5171.2 2162.39  5193.9 2163.08
  5209.9 2163.96  5222.2 2165.49  5244.9 2166.42  5254.1 2167.69  5276.3 2168.73
#Mann=3,-1,0
  4562.3    0.07       0  4995.7    0.07       0  4999.7    0.07       0
Bank Sta=4995.7,4999.7
Exp/Cntr=0.3,0.1

Type RM Length L Ch R = 1,3515,497,497,497
BEGIN DESCRIPTION:
Sweetwater Creek Trib 18 5.0
END DESCRIPTION:
XS GIS Cut Line= 3
      1375955.03      6841138.02      1376254.35      6841358.23
      1376805.00      6840738.00
#Sta/Elev= 30
  4628.4 2162.69  4665.0 2160.79  4692.0 2157.10  4715.1 2158.86  4736.0 2154.62
  4764.9 2156.01  4777.7 2153.60  4821.6 2149.47  4892.6 2146.90  4942.7 2147.50
  4990.9 2145.41  4991.1 2144.91  4994.9 2145.41  5022.0 2145.43  5064.6 2148.13
  5120.7 2146.90  5248.6 2149.41  5297.9 2148.73  5383.2 2152.20  5432.6 2152.47
  5446.8 2153.23  5461.0 2156.55  5481.9 2154.46  5510.4 2155.03  5546.3 2158.74
  5630.8 2164.09  5716.1 2167.72  5722.8 2166.78  5772.9 2172.46  5829.4 2176.21
#Mann=3,-1,0
  4628.4    0.07       0  4990.9    0.07       0  4994.9    0.07       0
Bank Sta=4990.9,4994.9
Exp/Cntr=0.3,0.1

Type RM Length L Ch R = 1,3018,0,0,0
BEGIN DESCRIPTION:
Sweetwater Creek Trib 18 2933
END DESCRIPTION:
XS GIS Cut Line= 3
      1375654.97      6841638.00      1376541.02      6841724.94
      1376655.00      6841138.00
#Sta/Elev= 30
  4109.7 2157.12  4210.2 2152.53  4264.4 2148.26  4270.5 2147.04  4330.8 2143.92
  4350.9 2141.85  4365.8 2144.18  4371.0 2142.60  4381.0 2141.78  4461.4 2141.17
  4481.5 2140.04  4592.0 2140.01  4622.2 2141.38  4675.2 2139.27  4732.7 2139.77
  4977.5 2137.79  4977.8 2137.29  4981.5 2137.79  5139.5 2139.21  5180.2 2141.37
  5205.1 2140.17  5384.0 2142.03  5411.9 2143.76  5417.0 2142.98  5424.7 2144.04
  5468.7 2143.62  5496.0 2144.74  5520.4 2144.65  5557.2 2147.12  5597.9 2147.78
#Mann=3,-1,0
  4109.7    0.07       0  4977.5    0.07       0  4981.5    0.07       0
Bank Sta=4977.5,4981.5
Exp/Cntr=0.3,0.1

Chan Stop Cuts=-1