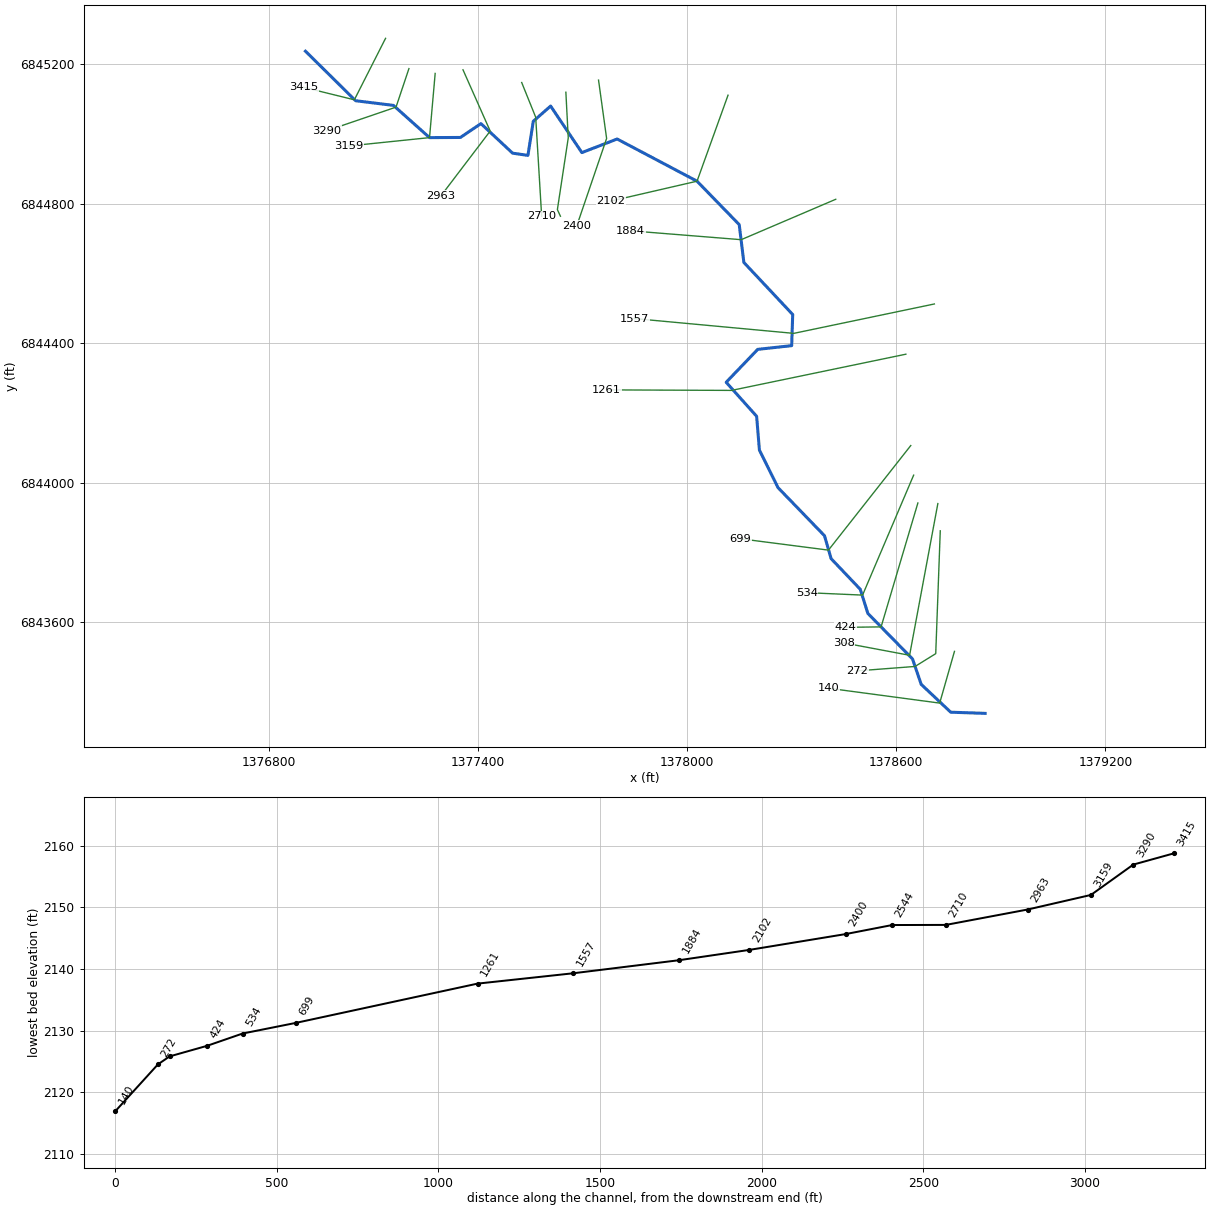
--- Sweetwater Creek Trib 19.prj (project) ---

Proj Title=Sweetwater Creek Trib 19 Base Level Engineering
Current Plan=p01
Default Exp/Contr=0.3,0.1
English Units
Geom File=g01
Flow File=f01
Plan File=p01
BEGIN DESCRIPTION:
Sweetwater Creek Trib 19
END DESCRIPTION:

--- Sweetwater Creek Trib 19.p01 (plan) ---

Plan Title=Multiple Run
Short Identifier=Multiple
Geom File=g01
Flow File=f01
Subcritical Flow
K Sum by GR= 0
Std Step Tol= 0.01
Critical Tol= 0.01
Num of Std Step Trials= 20
Max Error Tol= 0.3
Flow Tol Ratio= 0.001
Split Flow NTrial= 30
Split Flow Tol= 0.02
Split Flow Ratio= 0.02
Log Output Level= 0
Friction Slope Method= 1
Unsteady Friction Slope Method= 2
Unsteady Bridges Friction Slope Method= 1
Parabolic Critical Depth
Global Vel Dist=  1 , 1 , 1
Global Log Level= 0
CheckData=True
Encroach Param= -1, 0, 0, 0
BEGIN DESCRIPTION:
Multiple Run
END DESCRIPTION:

--- Sweetwater Creek Trib 19.f01 (steady flow) ---

Flow Title=Multiple
Number of Profiles=7
Profile Names=10-year,25-year,50-year,1pct_min,100-year,1pct_plu,500-year
River Rch & RM= Sweetwater Creek,Reach-1,3415
      99     132     158      95     189     376     273
Boundary for River Rch & Prof#=Sweetwater Creek,Reach-1,1
Up Type=0
Dn Type=3
Dn Slope=0.005
Boundary for River Rch & Prof#=Sweetwater Creek,Reach-1,2
Up Type=0
Dn Type=3
Dn Slope=0.005
Boundary for River Rch & Prof#=Sweetwater Creek,Reach-1,3
Up Type=0
Dn Type=3
Dn Slope=0.005
Boundary for River Rch & Prof#=Sweetwater Creek,Reach-1,4
Up Type=0
Dn Type=3
Dn Slope=0.005
Boundary for River Rch & Prof#=Sweetwater Creek,Reach-1,5
Up Type=0
Dn Type=3
Dn Slope=0.005
Boundary for River Rch & Prof#=Sweetwater Creek,Reach-1,6
Up Type=0
Dn Type=3
Dn Slope=0.005
Boundary for River Rch & Prof#=Sweetwater Creek,Reach-1,7
Up Type=0
Dn Type=3
Dn Slope=0.005

--- Sweetwater Creek Trib 19.g01 (geometry) ---

Geom Title=Existing Conditions

River Reach=Sweetwater Creek,Reach-1
Reach XY= 30
      1376905.00      6845238.00      1377048.83      6845095.86
      1377157.42      6845082.46      1377260.90      6844989.98
      1377349.52      6844990.49      1377408.41      6845030.19
      1377499.30      6844945.36      1377543.26      6844939.01
      1377558.65      6845036.91      1377608.38      6845080.60
      1377697.99      6844947.04      1377799.28      6844986.04
      1378028.47      6844864.99      1378149.48      6844740.43
      1378162.86      6844631.83      1378302.97      6844482.42
      1378300.05      6844393.11      1378202.61      6844382.45
      1378112.08      6844288.02      1378199.45      6844190.43
      1378207.45      6844093.56      1378260.83      6843985.70
      1378394.22      6843847.68      1378413.18      6843781.96
      1378496.82      6843694.04      1378518.63      6843624.79
      1378646.84      6843494.05      1378671.63      6843421.29
      1378756.39      6843341.38      1378855.00      6843338.00

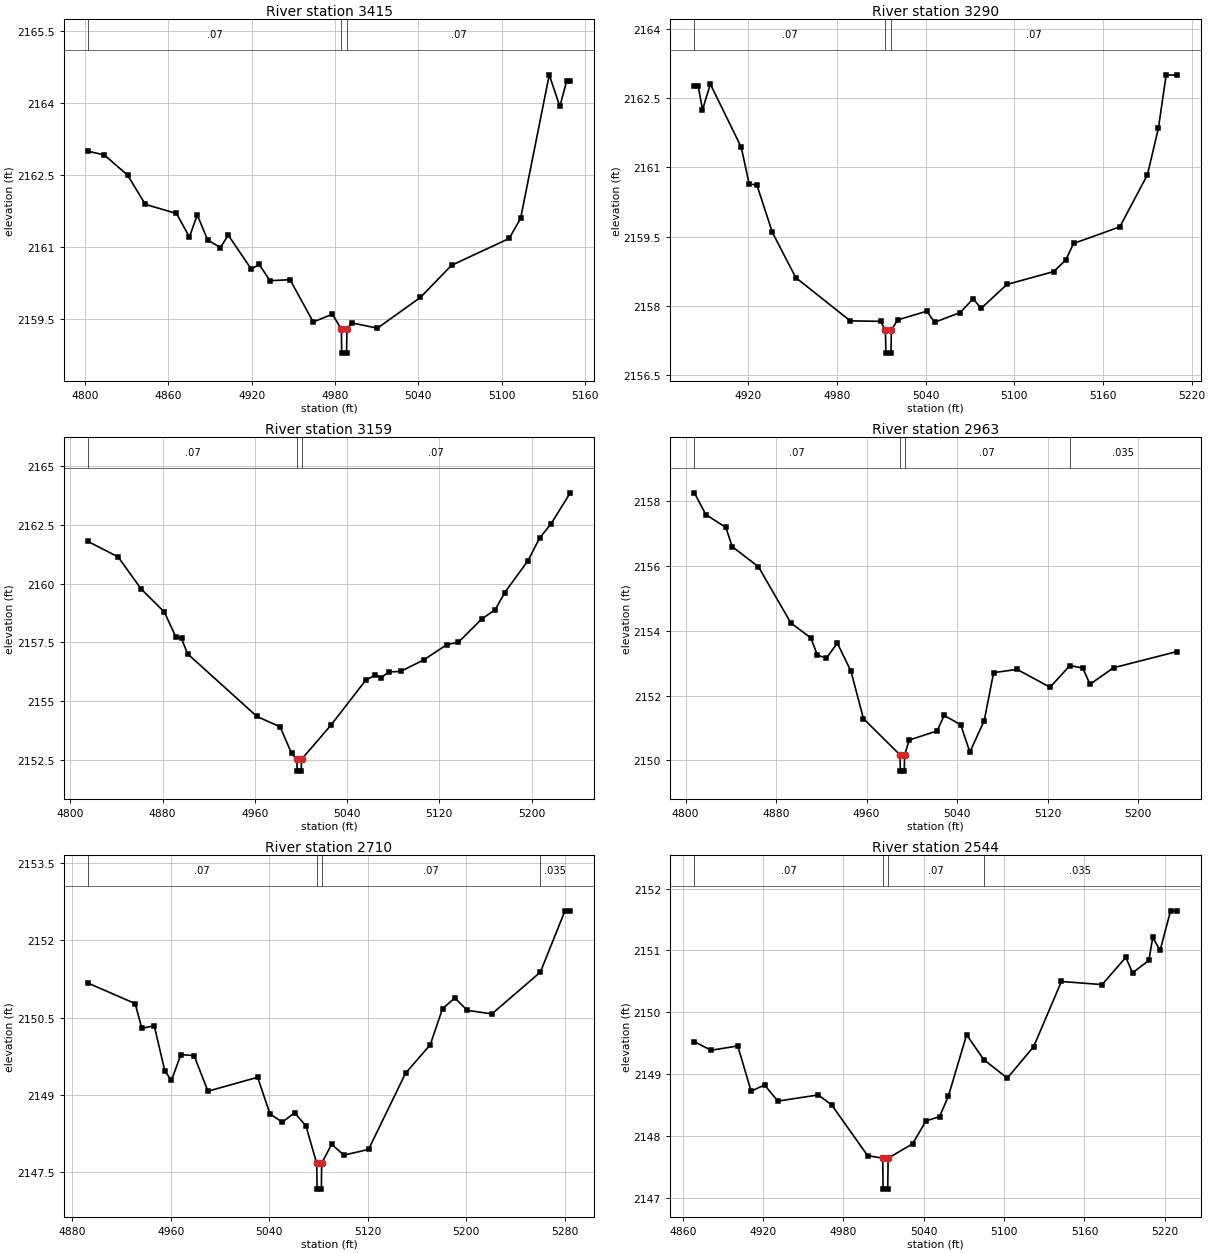
Type RM Length L Ch R = 1,3415,125,125,125
BEGIN DESCRIPTION:
Sweetwater Creek Trib 19 4271
END DESCRIPTION:
XS GIS Cut Line= 3
      1377134.76      6845274.88      1377045.21      6845098.51
      1376900.35      6845134.22
#Sta/Elev= 30
  4802.2 2163.00  4814.1 2162.92  4830.8 2162.50  4843.6 2161.89  4866.0 2161.70
  4875.3 2161.21  4880.9 2161.67  4888.4 2161.15  4897.6 2160.99  4903.2 2161.25
  4919.8 2160.54  4925.4 2160.64  4933.3 2160.30  4947.7 2160.32  4964.3 2159.44
  4978.1 2159.60  4984.6 2159.29  4984.8 2158.79  4988.3 2158.79  4988.6 2159.29
  4992.2 2159.42  5010.5 2159.31  5041.4 2159.95  5063.8 2160.62  5105.3 2161.18
  5113.5 2161.60  5134.1 2164.59  5141.7 2163.93  5146.6 2164.46  5149.2 2164.46
#Mann=3,-1,0
  4802.2    0.07       0  4984.6    0.07       0  4988.6    0.07       0
Bank Sta=4984.6,4988.6
Exp/Cntr=0.3,0.1

Type RM Length L Ch R = 1,3290,131,131,131
BEGIN DESCRIPTION:
Sweetwater Creek Trib 19 4489
END DESCRIPTION:
XS GIS Cut Line= 3
      1377201.81      6845188.02      1377164.78      6845077.46
      1376966.13      6845009.64
#Sta/Elev= 30
  4883.4 2162.77  4886.0 2162.77  4888.9 2162.25  4894.2 2162.81  4915.1 2161.44
  4920.5 2160.64  4925.7 2160.62  4936.2 2159.59  4952.0 2158.61  4988.9 2157.67
  5009.4 2157.66  5012.7 2157.47  5013.0 2156.97  5016.5 2156.97  5016.7 2157.47
  5020.9 2157.69  5040.7 2157.88  5046.0 2157.64  5063.2 2157.85  5072.1 2158.15
  5077.4 2157.94  5094.9 2158.46  5126.6 2158.74  5134.7 2158.99  5140.0 2159.35
  5171.3 2159.71  5190.0 2160.84  5197.4 2161.85  5202.7 2163.01  5209.9 2163.00
#Mann=3,-1,0
  4883.4    0.07       0  5012.7    0.07       0  5016.7    0.07       0
Bank Sta=5012.7,5016.7
Exp/Cntr=0.3,0.1

Type RM Length L Ch R = 1,3159,196,196,196
BEGIN DESCRIPTION:
Sweetwater Creek Trib 19 4270
END DESCRIPTION:
XS GIS Cut Line= 3
      1377277.11      6845174.16      1377260.90      6844989.98
      1377028.53      6844965.96
#Sta/Elev= 30
  4815.1 2161.79  4841.4 2161.13  4861.4 2159.77  4881.5 2158.79  4891.4 2157.74
  4896.4 2157.67  4901.6 2157.02  4961.8 2154.36  4981.9 2153.92  4991.9 2152.79
  4996.5 2152.54  4996.7 2152.04  5000.2 2152.04  5000.5 2152.54  5026.0 2153.99
  5056.2 2155.90  5064.5 2156.12  5069.6 2156.01  5076.3 2156.25  5086.4 2156.27
  5106.5 2156.76  5126.6 2157.41  5136.6 2157.51  5156.7 2158.49  5168.5 2158.89
  5176.8 2159.62  5196.9 2160.97  5207.0 2161.93  5217.0 2162.54  5233.6 2163.85
#Mann=3,-1,0
  4815.1    0.07       0  4996.5    0.07       0  5000.5    0.07       0
Bank Sta=4996.5,5000.5
Exp/Cntr=0.3,0.1

Type RM Length L Ch R = 1,2963,253,253,253
BEGIN DESCRIPTION:
Sweetwater Creek Trib 19 4269
END DESCRIPTION:
XS GIS Cut Line= 3
      1377356.95      6845184.60      1377435.00      6845008.85
      1377293.20      6844822.33
#Sta/Elev= 30
  4807.7 2158.26  4817.8 2157.59  4835.6 2157.19  4841.1 2156.60  4864.3 2155.98
  4893.1 2154.24  4910.8 2153.78  4916.3 2153.26  4924.3 2153.15  4934.1 2153.62
  4946.2 2152.75  4957.2 2151.29  4989.6 2150.17  4989.8 2149.67  4993.3 2149.67
  4993.6 2150.17  4997.7 2150.63  5022.3 2150.91  5028.6 2151.39  5043.2 2151.10
  5051.3 2150.26  5064.0 2151.23  5072.3 2152.71  5093.1 2152.81  5122.2 2152.26
  5139.8 2152.93  5151.2 2152.85  5157.5 2152.35  5178.3 2152.86  5234.3 2153.36
#Mann=4,-1,0
  4807.7    0.07       0  4989.6    0.07       0  4993.6    0.07       0
  5139.8   0.035       0
Bank Sta=4989.6,4993.6
Exp/Cntr=0.3,0.1

Type RM Length L Ch R = 1,2710,166,166,166
BEGIN DESCRIPTION:
Sweetwater Creek Trib 19 4267
END DESCRIPTION:
XS GIS Cut Line= 3
      1377525.37      6845148.10      1377565.56      6845048.50
      1377582.66      6844764.42
#Sta/Elev= 30
  4892.6 2151.17  4931.1 2150.77  4936.5 2150.29  4946.6 2150.34  4955.2 2149.46
  4960.6 2149.28  4968.2 2149.78  4979.0 2149.76  4990.2 2149.07  5030.6 2149.34
  5040.6 2148.63  5050.6 2148.47  5060.6 2148.65  5069.8 2148.40  5078.6 2147.67
  5078.9 2147.17  5082.4 2147.17  5082.6 2147.67  5090.7 2148.04  5100.7 2147.83
  5120.7 2147.94  5150.8 2149.42  5170.8 2149.97  5180.8 2150.67  5190.8 2150.88
  5200.9 2150.64  5220.9 2150.57  5260.3 2151.38  5280.3 2152.57  5284.6 2152.57
#Mann=4,-1,0
  4892.6    0.07       0  5078.6    0.07       0  5082.6    0.07       0
  5260.3   0.035       0
Bank Sta=5078.6,5082.6
Exp/Cntr=0.3,0.1

Type RM Length L Ch R = 1,2544,144,144,144
BEGIN DESCRIPTION:
Sweetwater Creek Trib 19 4268
END DESCRIPTION:
XS GIS Cut Line= 4
      1377652.11      6845120.35      1377658.97      6844989.23
      1377627.80      6844783.52      1377636.47      6844764.46
#Sta/Elev= 30
  4868.7 2149.53  4881.1 2149.39  4901.1 2149.46  4911.1 2148.73  4921.1 2148.83
  4931.1 2148.57  4961.2 2148.67  4971.2 2148.51  4998.1 2147.69  5009.4 2147.65
  5009.6 2147.15  5013.1 2147.15  5013.4 2147.65  5031.6 2147.88  5041.7 2148.25
  5051.8 2148.32  5058.4 2148.65  5072.0 2149.64  5084.8 2149.24  5102.4 2148.94
  5122.1 2149.45  5142.8 2150.50  5173.2 2150.45  5190.9 2150.89  5195.9 2150.64
  5208.1 2150.84  5211.0 2151.21  5216.5 2151.00  5224.3 2151.64  5229.0 2151.64
#Mann=4,-1,0
  4868.7    0.07       0  5009.4    0.07       0  5013.4    0.07       0
  5084.8   0.035       0
Bank Sta=5009.4,5013.4
Exp/Cntr=0.3,0.1

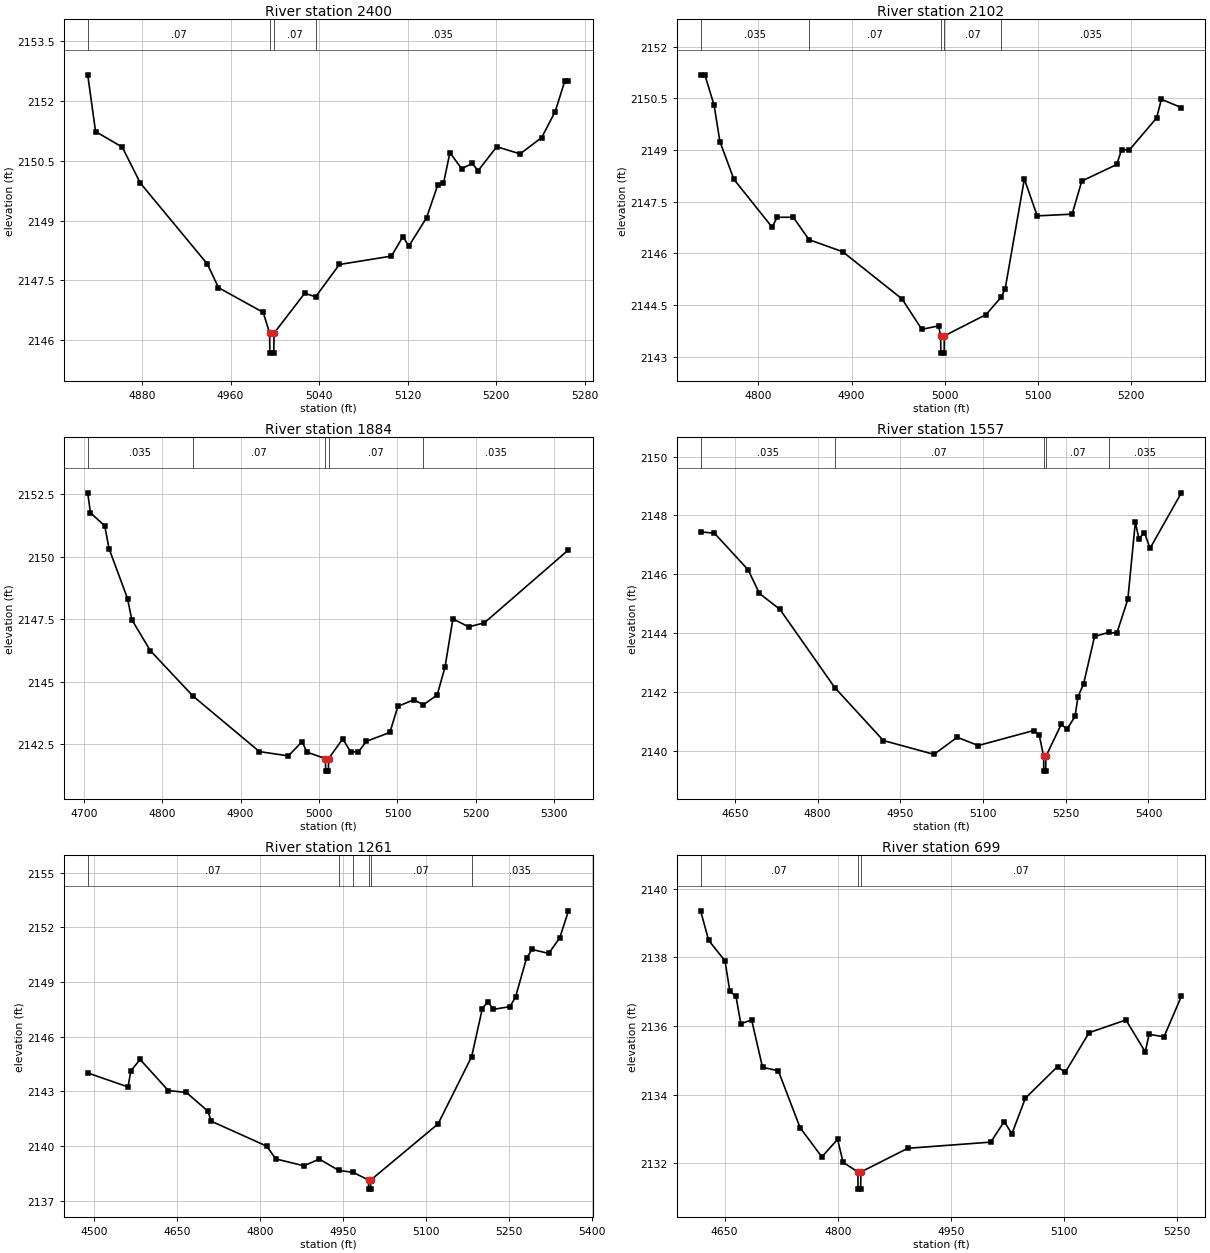
Type RM Length L Ch R = 1,2400,298,298,298
BEGIN DESCRIPTION:
Sweetwater Creek Trib 19 4266
END DESCRIPTION:
XS GIS Cut Line= 3
      1377745.86      6845155.01      1377769.04      6844987.61
      1377683.35      6844736.63
#Sta/Elev= 30
  4831.0 2152.65  4838.1 2151.23  4862.2 2150.84  4878.5 2149.94  4939.1 2147.91
  4949.1 2147.32  4989.5 2146.70  4995.3 2146.18  4995.5 2145.68  4999.0 2145.68
  4999.3 2146.18  5027.0 2147.18  5036.8 2147.09  5058.3 2147.90  5105.3 2148.11
  5115.7 2148.60  5121.0 2148.36  5137.0 2149.07  5147.0 2149.88  5152.3 2149.93
  5158.1 2150.70  5168.7 2150.30  5178.3 2150.43  5183.6 2150.25  5200.4 2150.85
  5221.5 2150.67  5241.0 2151.08  5253.2 2151.73  5261.8 2152.49  5265.2 2152.49
#Mann=4,-1,0
  4831.0    0.07       0  4995.3    0.07       0  4999.3    0.07       0
  5036.8   0.035       0
Bank Sta=4995.3,4999.3
Exp/Cntr=0.3,0.1

Type RM Length L Ch R = 1,2102,218,218,218
BEGIN DESCRIPTION:
Sweetwater Creek Trib 19 4265
END DESCRIPTION:
XS GIS Cut Line= 3
      1378117.39      6845111.65      1378028.47      6844864.99
      1377780.58      6844807.83
#Sta/Elev= 30
  4737.8 2151.18  4742.4 2151.18  4752.3 2150.30  4758.6 2149.24  4773.6 2148.15
  4814.7 2146.76  4820.0 2147.05  4837.4 2147.05  4854.3 2146.40  4890.5 2146.05
  4954.3 2144.68  4975.5 2143.80  4993.5 2143.90  4995.7 2143.61  4996.0 2143.11
  4999.5 2143.11  4999.7 2143.61  5044.6 2144.23  5060.7 2144.73  5065.1 2144.98
  5085.7 2148.16  5099.5 2147.09  5137.0 2147.14  5147.4 2148.10  5185.0 2148.58
  5190.1 2149.01  5198.5 2149.00  5227.8 2149.93  5232.9 2150.47  5254.4 2150.23
#Mann=5,-1,0
  4737.8   0.035       0  4854.3    0.07       0  4995.7    0.07       0
  4999.7    0.07       0  5060.7   0.035       0
Bank Sta=4995.7,4999.7
Exp/Cntr=0.3,0.1

Type RM Length L Ch R = 1,1884,327,327,327
BEGIN DESCRIPTION:
Sweetwater Creek Trib 19 4264
END DESCRIPTION:
XS GIS Cut Line= 3
      1378426.43      6844813.04      1378155.15      6844697.15
      1377838.07      6844722.60
#Sta/Elev= 30
  4705.0 2152.56  4708.5 2151.76  4726.7 2151.24  4732.2 2150.33  4755.8 2148.33
  4761.2 2147.49  4784.8 2146.25  4839.3 2144.43  4924.0 2142.21  4960.9 2142.04
  4978.4 2142.61  4984.5 2142.19  5008.2 2141.93  5008.4 2141.43  5011.9 2141.43
  5012.2 2141.93  5030.2 2142.72  5040.3 2142.20  5050.3 2142.20  5060.3 2142.62
  5090.4 2142.98  5100.5 2144.02  5120.5 2144.28  5133.2 2144.09  5150.6 2144.47
  5160.7 2145.60  5170.7 2147.52  5190.8 2147.20  5210.8 2147.36  5318.1 2150.28
#Mann=5,-1,0
  4705.0   0.035       0  4839.3    0.07       0  5008.2    0.07       0
  5012.2    0.07       0  5133.2   0.035       0
Bank Sta=5008.2,5012.2
Exp/Cntr=0.3,0.1

Type RM Length L Ch R = 1,1557,296,296,296
BEGIN DESCRIPTION:
Sweetwater Creek Trib 19 4263
END DESCRIPTION:
XS GIS Cut Line= 3
      1378709.43      6844512.70      1378306.05      6844428.36
      1377848.32      6844470.86
#Sta/Elev= 30
  4587.9 2147.44  4612.9 2147.40  4674.2 2146.15  4694.6 2145.35  4731.7 2144.81
  4831.2 2142.15  4919.3 2140.35  5011.1 2139.88  5053.2 2140.46  5091.4 2140.18
  5191.9 2140.69  5201.9 2140.54  5210.0 2139.81  5210.2 2139.31  5213.7 2139.31
  5214.0 2139.81  5242.1 2140.91  5252.1 2140.73  5266.9 2141.17  5272.2 2141.84
  5282.3 2142.27  5302.3 2143.89  5329.0 2144.03  5342.5 2143.99  5362.6 2145.15
  5376.2 2147.77  5382.7 2147.21  5392.7 2147.42  5402.8 2146.88  5459.7 2148.77
#Mann=5,-1,0
  4587.9   0.035       0  4831.2    0.07       0  5210.0    0.07       0
  5214.0    0.07       0  5329.0   0.035       0
Bank Sta=5210,5214
Exp/Cntr=0.3,0.1

Type RM Length L Ch R = 1,1261,562,562,562
BEGIN DESCRIPTION:
Sweetwater Creek Trib 19 4262
END DESCRIPTION:
XS GIS Cut Line= 3
      1378627.76      6844368.58      1378127.44      6844264.69
      1377769.24      6844266.16
#Sta/Elev= 30
  4489.0 2144.01  4561.9 2143.24  4567.0 2144.12  4583.7 2144.75  4634.8 2143.04
  4667.3 2142.94  4706.3 2141.91  4712.3 2141.36  4812.6 2139.99  4828.9 2139.29
  4879.9 2138.91  4907.7 2139.28  4942.7 2138.66  4968.8 2138.55  4996.7 2138.13
  4996.9 2137.63  5000.4 2137.63  5000.7 2138.13  5122.4 2141.21  5183.1 2144.90
  5202.4 2147.54  5212.4 2147.93  5222.4 2147.50  5252.4 2147.65  5262.4 2148.17
  5282.4 2150.32  5292.4 2150.79  5322.4 2150.57  5342.4 2151.43  5358.2 2152.91
#Mann=6,-1,0
  4489.0    0.07       0  4942.7    0.16       0  4968.8    0.07       0
  4996.7    0.07       0  5000.7    0.07       0  5183.1   0.035       0
Bank Sta=4996.7,5000.7
Exp/Cntr=0.3,0.1

Type RM Length L Ch R = 1,699,165,165,165
BEGIN DESCRIPTION:
Sweetwater Creek Trib 19 4260
END DESCRIPTION:
XS GIS Cut Line= 3
      1378641.69      6844106.43      1378405.55      6843806.41
      1378152.15      6843839.07
#Sta/Elev= 30
  4618.2 2139.36  4628.9 2138.50  4650.6 2137.90  4657.0 2137.01  4665.1 2136.87
  4671.5 2136.07  4685.9 2136.18  4700.3 2134.80  4721.2 2134.70  4750.1 2133.04
  4778.9 2132.19  4799.8 2132.70  4807.1 2132.03  4826.7 2131.75  4826.9 2131.25
  4830.4 2131.25  4830.7 2131.75  4892.8 2132.44  5002.8 2132.62  5020.7 2133.22
  5030.8 2132.86  5048.7 2133.90  5091.3 2134.82  5101.4 2134.65  5133.2 2135.81
  5182.0 2136.18  5207.6 2135.25  5212.7 2135.76  5232.5 2135.69  5255.5 2136.87
#Mann=3,-1,0
  4618.2    0.07       0  4826.7    0.07       0  4830.7    0.07       0
Bank Sta=4826.7,4830.7
Exp/Cntr=0.3,0.1

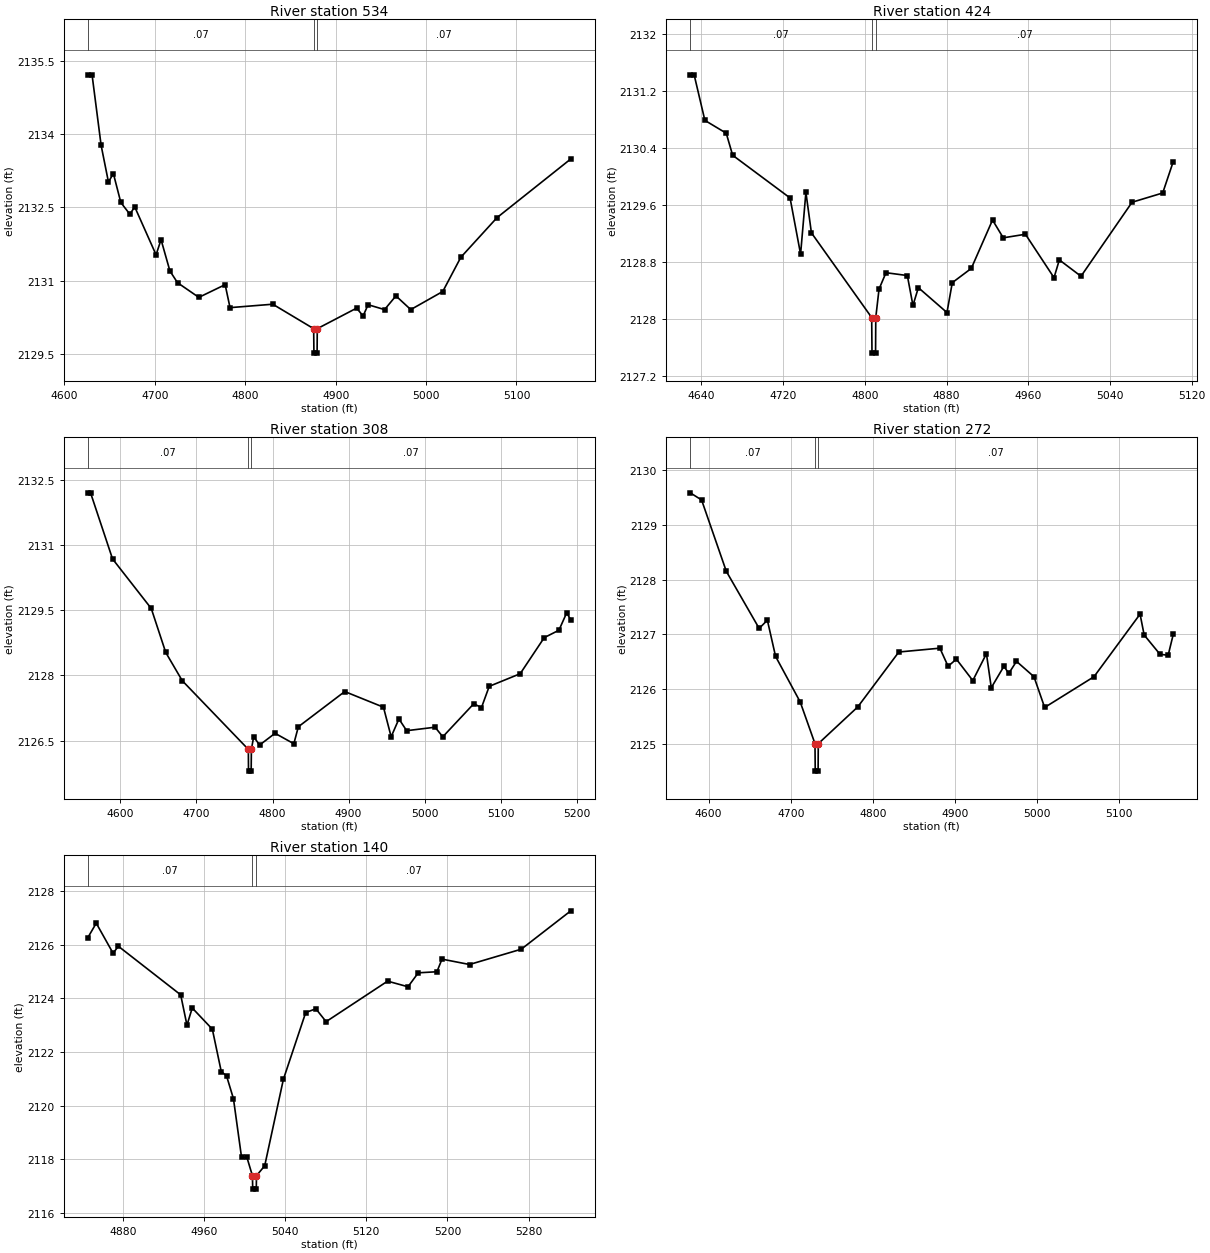
Type RM Length L Ch R = 1,534,110,110,110
BEGIN DESCRIPTION:
Sweetwater Creek Trib 19 4259
END DESCRIPTION:
XS GIS Cut Line= 3
      1378650.00      6844021.55      1378503.44      6843677.36
      1378343.50      6843684.35
#Sta/Elev= 30
  4625.9 2135.21  4630.6 2135.21  4640.6 2133.77  4648.7 2133.02  4654.2 2133.19
  4662.4 2132.60  4672.4 2132.36  4677.8 2132.51  4701.4 2131.53  4706.9 2131.84
  4716.7 2131.20  4725.1 2130.96  4748.7 2130.66  4777.8 2130.92  4783.2 2130.45
  4830.5 2130.52  4875.7 2130.02  4876.0 2129.52  4879.5 2129.52  4879.7 2130.02
  4923.2 2130.44  4930.4 2130.28  4935.9 2130.51  4954.1 2130.41  4966.7 2130.69
  4983.1 2130.41  5018.5 2130.78  5038.5 2131.48  5078.5 2132.29  5160.1 2133.49
#Mann=3,-1,0
  4625.9    0.07       0  4875.7    0.07       0  4879.7    0.07       0
Bank Sta=4875.7,4879.7
Exp/Cntr=0.3,0.1

Type RM Length L Ch R = 1,424,116,116,116
BEGIN DESCRIPTION:
Sweetwater Creek Trib 19 4485
END DESCRIPTION:
XS GIS Cut Line= 3
      1378662.15      6843941.70      1378556.59      6843586.14
      1378454.70      6843584.90
#Sta/Elev= 30
  4629.1 2131.43  4632.9 2131.43  4643.4 2130.79  4664.3 2130.61  4670.6 2130.30
  4726.8 2129.70  4737.1 2128.91  4742.3 2129.78  4747.7 2129.21  4806.7 2128.02
  4807.0 2127.52  4810.5 2127.52  4810.7 2128.02  4813.9 2128.42  4820.7 2128.65
  4841.6 2128.61  4847.1 2128.19  4852.4 2128.44  4880.4 2128.09  4885.6 2128.51
  4904.2 2128.71  4925.0 2129.39  4935.5 2129.14  4957.2 2129.19  4985.2 2128.58
  4990.4 2128.83  5011.6 2128.60  5061.6 2129.64  5091.6 2129.77  5101.9 2130.21
#Mann=3,-1,0
  4629.1    0.07       0  4806.7    0.07       0  4810.7    0.07       0
Bank Sta=4806.7,4810.7
Exp/Cntr=0.3,0.1

Type RM Length L Ch R = 1,308,36,36,36
BEGIN DESCRIPTION:
Sweetwater Creek Trib 19 4258
END DESCRIPTION:
XS GIS Cut Line= 3
      1378719.45      6843939.98      1378638.35      6843504.67
      1378449.66      6843540.20
#Sta/Elev= 30
  4557.2 2132.20  4560.8 2132.20  4589.7 2130.68  4640.6 2129.54  4659.6 2128.53
  4681.3 2127.88  4768.2 2126.30  4768.4 2125.80  4771.9 2125.80  4772.2 2126.30
  4775.2 2126.59  4783.0 2126.40  4803.3 2126.67  4828.0 2126.43  4833.9 2126.82
  4894.9 2127.63  4945.8 2127.27  4955.9 2126.59  4966.1 2127.00  4976.3 2126.73
  5013.6 2126.81  5023.8 2126.59  5064.5 2127.35  5074.6 2127.26  5084.8 2127.75
  5125.5 2128.04  5157.1 2128.87  5176.4 2129.04  5186.6 2129.44  5192.0 2129.28
#Mann=3,-1,0
  4557.2    0.07       0  4768.2    0.07       0  4772.2    0.07       0
Bank Sta=4768.2,4772.2
Exp/Cntr=0.3,0.1

Type RM Length L Ch R = 1,272,132,132,132
BEGIN DESCRIPTION:
Sweetwater Creek Trib 19 4486
END DESCRIPTION:
XS GIS Cut Line= 4
      1378726.38      6843861.84      1378713.36      6843509.38
      1378654.13      6843472.64      1378488.81      6843459.99
#Sta/Elev= 30
  4577.6 2129.58  4591.4 2129.45  4621.5 2128.15  4661.5 2127.11  4671.5 2127.26
  4681.5 2126.60  4711.5 2125.77  4729.5 2125.01  4729.8 2124.51  4733.3 2124.51
  4733.5 2125.01  4781.6 2125.68  4831.6 2126.68  4881.6 2126.75  4891.6 2126.42
  4901.7 2126.55  4921.7 2126.16  4938.3 2126.65  4944.2 2126.03  4959.6 2126.42
  4965.5 2126.29  4974.9 2126.51  4996.2 2126.23  5009.2 2125.67  5069.3 2126.23
  5125.4 2127.37  5130.4 2126.99  5149.6 2126.64  5159.6 2126.62  5165.8 2127.00
#Mann=3,-1,0
  4577.6    0.07       0  4729.5    0.07       0  4733.5    0.07       0
Bank Sta=4729.5,4733.5
Exp/Cntr=0.3,0.1

Type RM Length L Ch R = 1,140,0,0,0
BEGIN DESCRIPTION:
Sweetwater Creek Trib 19 4257
END DESCRIPTION:
XS GIS Cut Line= 3
      1378767.13      6843515.96      1378724.73      6843367.50
      1378406.06      6843410.04
#Sta/Elev= 30
  4845.6 2126.26  4853.9 2126.80  4870.5 2125.68  4875.7 2125.94  4937.1 2124.13
  4943.3 2123.00  4948.5 2123.64  4968.3 2122.85  4977.1 2121.27  4982.3 2121.11
  4989.1 2120.26  4997.1 2118.07  5002.4 2118.07  5007.8 2117.39  5008.1 2116.89
  5011.6 2116.89  5011.8 2117.39  5019.9 2117.76  5038.3 2120.98  5060.3 2123.47
  5070.3 2123.61  5080.4 2123.13  5141.0 2124.64  5161.1 2124.43  5171.2 2124.95
  5189.6 2124.99  5194.6 2125.46  5221.7 2125.26  5272.7 2125.83  5321.5 2127.26
#Mann=3,-1,0
  4845.6    0.07       0  5007.8    0.07       0  5011.8    0.07       0
Bank Sta=5007.8,5011.8
Exp/Cntr=0.3,0.1

Chan Stop Cuts=-1