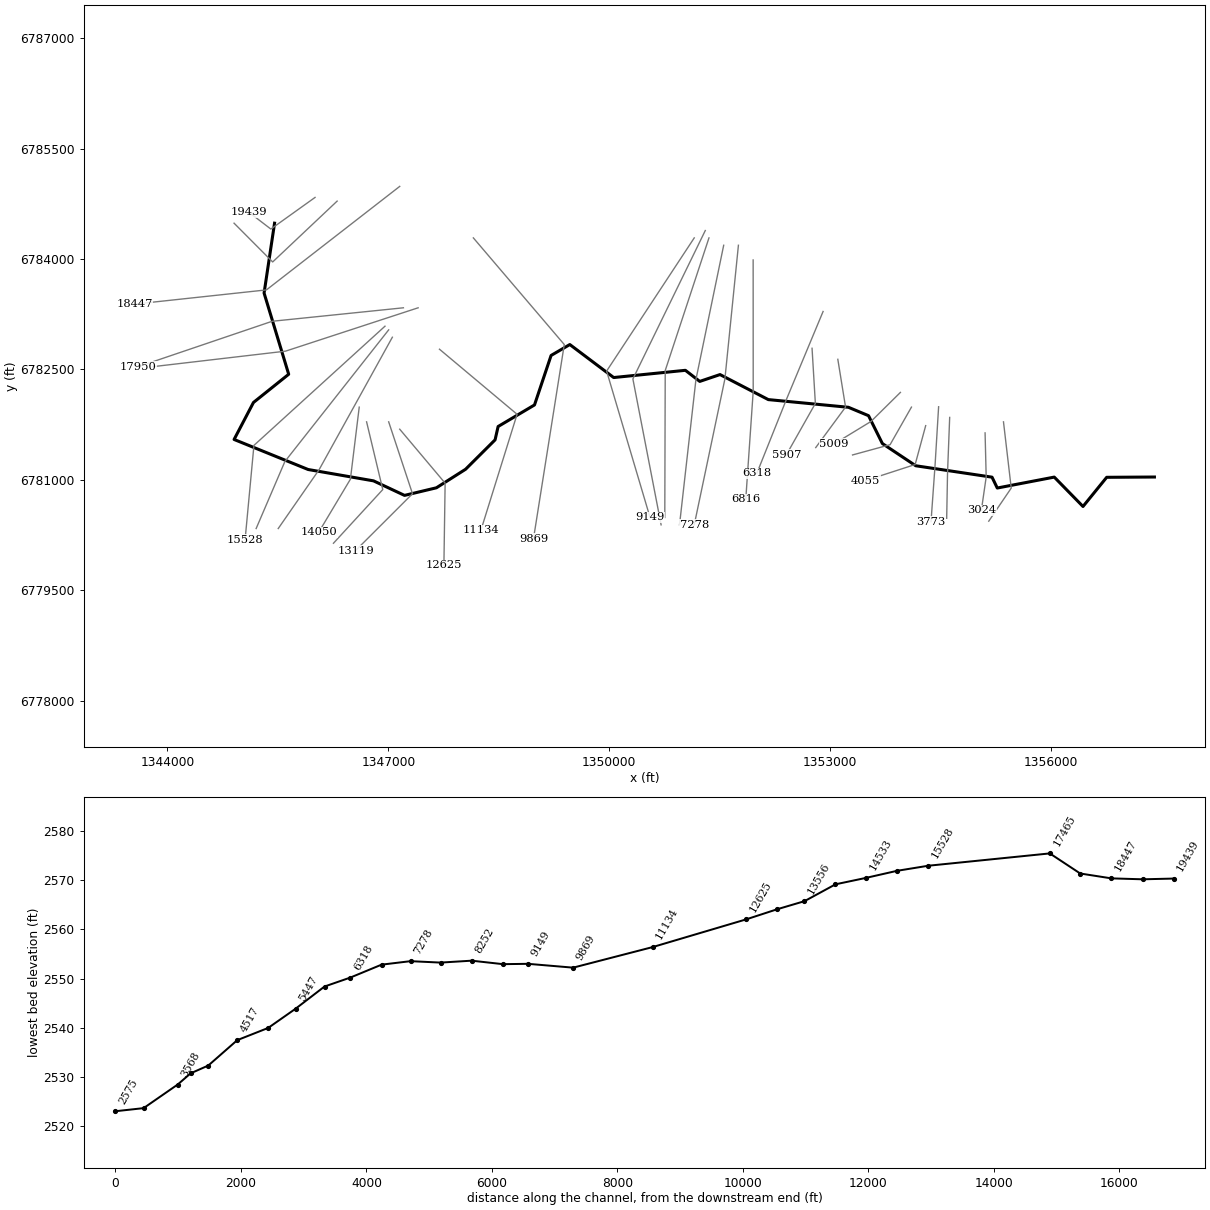
--- Sweetwater Creek Trib2.prj (project) ---

Proj Title=Sweetwater Creek Trib2 Base Level Engineering
Current Plan=p01
Default Exp/Contr=0.3,0.1
English Units
Geom File=g01
Flow File=f01
Plan File=p01
BEGIN DESCRIPTION:
Sweetwater Creek Trib2
END DESCRIPTION:

--- Sweetwater Creek Trib2.p01 (plan) ---

Plan Title=Multiple Run
Short Identifier=Multiple
Geom File=g01
Flow File=f01
Subcritical Flow
K Sum by GR= 0
Std Step Tol= 0.01
Critical Tol= 0.01
Num of Std Step Trials= 20
Max Error Tol= 0.3
Flow Tol Ratio= 0.001
Split Flow NTrial= 30
Split Flow Tol= 0.02
Split Flow Ratio= 0.02
Log Output Level= 0
Friction Slope Method= 1
Unsteady Friction Slope Method= 2
Unsteady Bridges Friction Slope Method= 1
Parabolic Critical Depth
Global Vel Dist=  1 , 1 , 1
Global Log Level= 0
CheckData=True
Encroach Param= -1, 0, 0, 0
BEGIN DESCRIPTION:
Multiple Run
END DESCRIPTION:

--- Sweetwater Creek Trib2.f01 (steady flow) ---

Flow Title=Multiple
Number of Profiles=7
Profile Names=10-year,25-year,50-year,1pct_min,100-year,1pct_plu,500-year
River Rch & RM= Sweetwater Creek,Reach-1,19439
     117     152     179     104     208     414     284
River Rch & RM= Sweetwater Creek,Reach-1,18447
     211     284     342     204     407     813     586
River Rch & RM= Sweetwater Creek,Reach-1,9869
     245     333     404     243     484     966     706
River Rch & RM= Sweetwater Creek,Reach-1,9149
     385     536     660     402     801    1599    1199
River Rch & RM= Sweetwater Creek,Reach-1,4055
     508     722     900     556    1109    2213    1708
River Rch & RM= Sweetwater Creek,Reach-1,1096
     603     866    1089     677    1352    2697    2113
Boundary for River Rch & Prof#=Sweetwater Creek,Reach-1,1
Up Type=0
Dn Type=3
Dn Slope=0.005
Boundary for River Rch & Prof#=Sweetwater Creek,Reach-1,2
Up Type=0
Dn Type=3
Dn Slope=0.005
Boundary for River Rch & Prof#=Sweetwater Creek,Reach-1,3
Up Type=0
Dn Type=3
Dn Slope=0.005
Boundary for River Rch & Prof#=Sweetwater Creek,Reach-1,4
Up Type=0
Dn Type=3
Dn Slope=0.005
Boundary for River Rch & Prof#=Sweetwater Creek,Reach-1,5
Up Type=0
Dn Type=3
Dn Slope=0.005
Boundary for River Rch & Prof#=Sweetwater Creek,Reach-1,6
Up Type=0
Dn Type=3
Dn Slope=0.005
Boundary for River Rch & Prof#=Sweetwater Creek,Reach-1,7
Up Type=0
Dn Type=3
Dn Slope=0.005

--- Sweetwater Creek Trib2.g01 (geometry) ---

Geom Title=Existing Conditions

River Reach=Sweetwater Creek,Reach-1
Reach XY= 30
      1345455.00      6784488.00      1345312.78      6783538.10
      1345647.02      6782434.67      1345168.62      6782051.22
      1344905.48      6781548.47      1345910.93      6781140.24
      1346799.15      6780985.94      1347220.28      6780788.38
      1347653.45      6780891.75      1348049.42      6781143.58
      1348449.99      6781543.01      1348491.37      6781724.54
      1348985.37      6782017.52      1349210.83      6782690.30
      1349465.19      6782838.55      1350060.85      6782390.06
      1351034.84      6782488.32      1351229.97      6782337.49
      1351505.00      6782430.45      1352160.94      6782090.26
      1353249.07      6781985.76      1353522.22      6781871.74
      1353710.11      6781493.11      1354163.30      6781191.07
      1355199.35      6781036.03      1355270.58      6780888.56
      1356044.57      6781036.96      1356434.87      6780637.59
      1356756.58      6781034.18      1357405.00      6781038.00

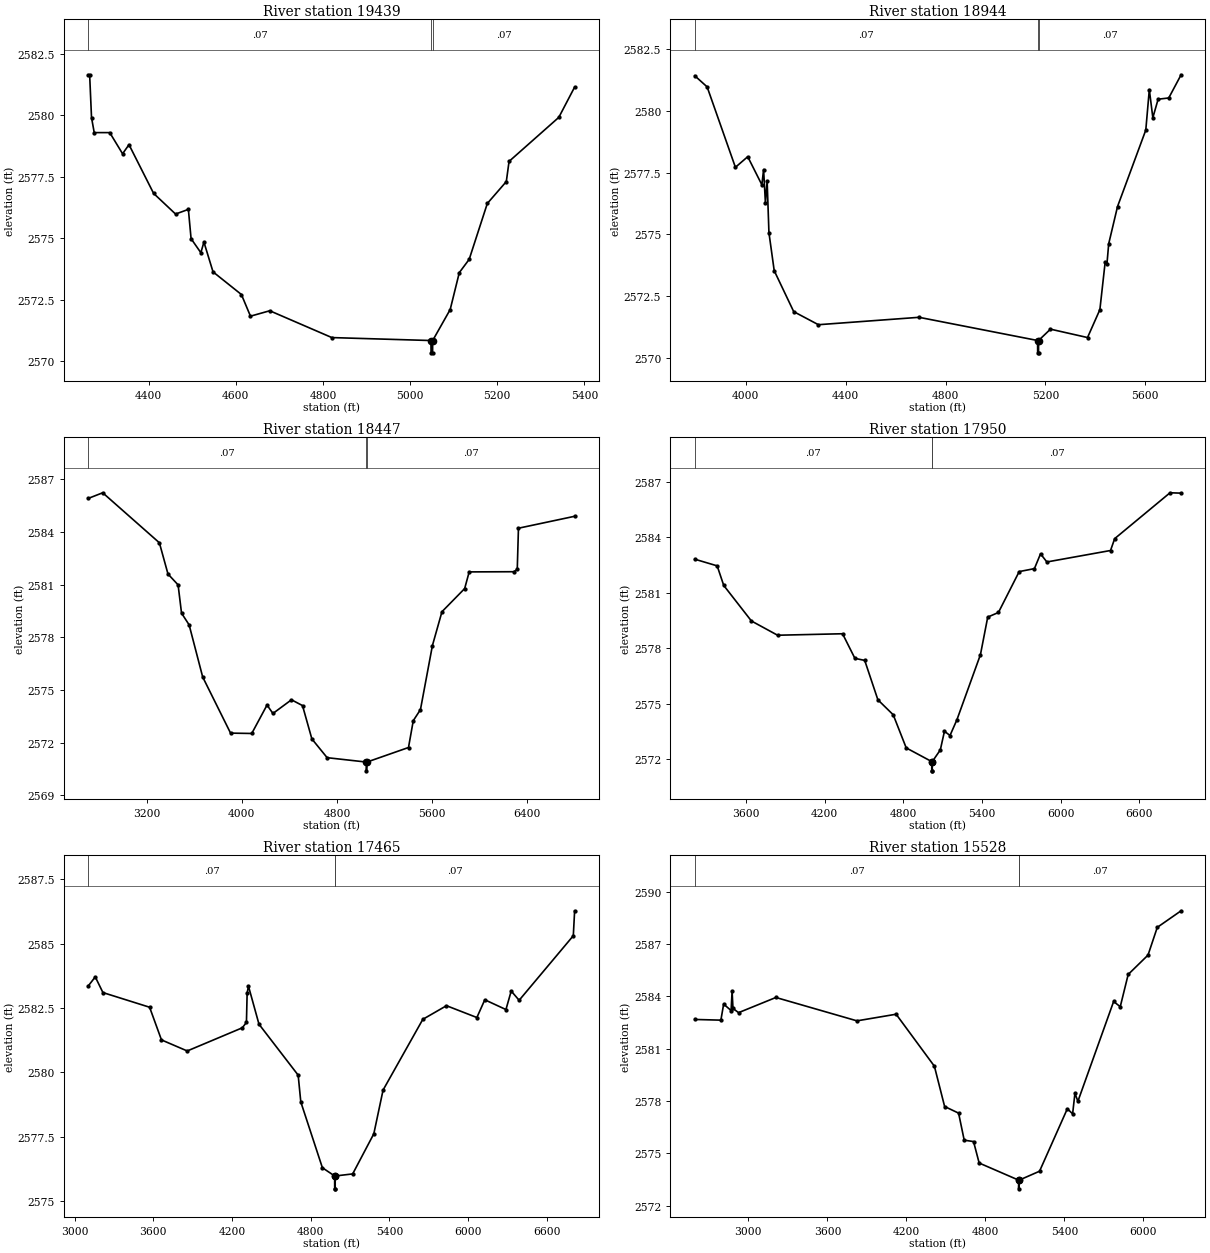
Type RM Length L Ch R = 1,19439,495,495,495
BEGIN DESCRIPTION:
Sweetwater Creek Trib2 30.0
END DESCRIPTION:
XS GIS Cut Line= 3
      1346005.03      6784838.02      1345404.59      6784408.06
      1345104.97      6784638.02
#Sta/Elev= 30
  4261.5 2581.65  4264.6 2581.65  4268.9 2579.91  4275.1 2579.30  4310.7 2579.30
  4340.2 2578.44  4354.9 2578.81  4411.4 2576.83  4461.8 2575.99  4491.2 2576.18
  4497.4 2574.99  4519.8 2574.42  4526.9 2574.85  4547.8 2573.64  4612.9 2572.72
  4633.7 2571.84  4678.0 2572.06  4820.5 2570.97  5047.9 2570.85  5048.2 2570.35
  5051.7 2570.35  5051.9 2570.85  5092.1 2572.11  5113.0 2573.61  5135.7 2574.15
  5177.3 2576.42  5220.9 2577.31  5227.2 2578.13  5341.4 2579.92  5377.7 2581.15
#Mann=3,-1,0
  4261.5    0.07       0  5047.9    0.07       0  5051.9    0.07       0
Bank Sta=5047.9,5051.9
Exp/Cntr=0.3,0.1

Type RM Length L Ch R = 1,18944,497,497,497
BEGIN DESCRIPTION:
Sweetwater Creek Trib2 29.0
END DESCRIPTION:
XS GIS Cut Line= 3
      1346304.99      6784787.99      1345429.41      6783961.00
      1344904.97      6784488.03
#Sta/Elev= 30
  3795.6 2581.43  3845.1 2580.98  3958.4 2577.72  4007.8 2578.15  4064.4 2577.01
  4071.3 2577.63  4078.6 2576.27  4085.5 2577.16  4092.7 2575.07  4113.8 2573.53
  4191.9 2571.87  4290.8 2571.34  4693.9 2571.64  5168.7 2570.70  5169.0 2570.20
  5172.5 2570.20  5172.7 2570.70  5220.2 2571.16  5368.7 2570.82  5418.2 2571.95
  5439.4 2573.88  5446.5 2573.80  5453.5 2574.62  5488.9 2576.13  5602.1 2579.23
  5616.2 2580.87  5630.3 2579.73  5651.5 2580.48  5694.0 2580.53  5743.5 2581.47
#Mann=3,-1,0
  3795.6    0.07       0  5168.7    0.07       0  5172.7    0.07       0
Bank Sta=5168.7,5172.7
Exp/Cntr=0.3,0.1

Type RM Length L Ch R = 1,18447,497,497,497
BEGIN DESCRIPTION:
Sweetwater Creek Trib2 28.0
END DESCRIPTION:
XS GIS Cut Line= 3
      1347155.01      6784988.01      1345345.06      6783581.34
      1343554.97      6783388.00
#Sta/Elev= 30
  2707.7 2585.92  2829.0 2586.24  3305.9 2583.39  3378.3 2581.61  3463.4 2580.99
  3492.3 2579.38  3556.3 2578.71  3670.3 2575.74  3905.0 2572.54  4083.3 2572.52
  4211.8 2574.14  4261.6 2573.66  4417.5 2574.44  4510.4 2574.11  4589.2 2572.21
  4717.7 2571.14  5048.3 2570.89  5048.6 2570.39  5052.5 2570.89  5402.4 2571.72
  5442.6 2573.25  5503.0 2573.88  5603.6 2577.53  5684.0 2579.46  5875.1 2580.78
  5913.1 2581.73  6290.4 2581.74  6317.7 2581.88  6327.7 2584.22  6800.5 2584.90
#Mann=3,-1,0
  2707.7    0.07       0  5048.3    0.07       0  5052.5    0.07       0
Bank Sta=5048.3,5052.5
Exp/Cntr=0.3,0.1

Type RM Length L Ch R = 1,17950,485,485,485
BEGIN DESCRIPTION:
Sweetwater Creek Trib2 27.0
END DESCRIPTION:
XS GIS Cut Line= 3
      1347205.03      6783338.00      1345422.33      6783154.75
      1343605.03      6782538.01
#Sta/Elev= 30
  3207.9 2582.82  3378.8 2582.46  3429.1 2581.40  3640.2 2579.48  3839.9 2578.71
  4335.7 2578.79  4429.9 2577.46  4504.7 2577.35  4605.3 2575.22  4722.3 2574.41
  4821.5 2572.62  5016.2 2571.88  5016.4 2571.38  5020.1 2571.38  5020.4 2571.88
  5081.7 2572.51  5113.3 2573.52  5155.6 2573.29  5208.4 2574.14  5387.9 2577.66
  5443.5 2579.69  5525.2 2579.94  5683.6 2582.15  5799.8 2582.31  5846.4 2583.11
  5894.8 2582.67  6380.6 2583.29  6412.2 2583.93  6834.6 2586.41  6919.1 2586.39
#Mann=3,-1,0
  3207.9    0.07       0  5016.2    0.07       0  5020.4    0.07       0
Bank Sta=5016.2,5020.4
Exp/Cntr=0.3,0.1

Type RM Length L Ch R = 1,17465,1937,1937,1937
BEGIN DESCRIPTION:
Sweetwater Creek Trib2 26.0
END DESCRIPTION:
XS GIS Cut Line= 3
      1347405.03      6783338.01      1345604.12      6782748.64
      1343805.00      6782538.00
#Sta/Elev= 30
  3105.1 2583.36  3158.2 2583.71  3216.6 2583.10  3572.3 2582.53  3662.7 2581.26
  3859.1 2580.83  4278.5 2581.73  4310.3 2581.94  4315.6 2583.08  4325.7 2583.35
  4405.9 2581.87  4704.5 2579.89  4724.5 2578.85  4889.1 2576.29  4982.5 2575.97
  4982.8 2575.47  4986.5 2575.47  4986.8 2575.97  5119.9 2576.05  5281.0 2577.61
  5351.5 2579.31  5654.5 2582.06  5834.8 2582.59  6066.4 2582.13  6126.8 2582.82
  6287.9 2582.44  6328.1 2583.16  6388.5 2582.80  6801.3 2585.31  6811.4 2586.28
#Mann=3,-1,0
  3105.1    0.07       0  4982.5    0.07       0  4986.8    0.07       0
Bank Sta=4982.5,4986.8
Exp/Cntr=0.3,0.1

Type RM Length L Ch R = 1,15528,496,496,496
BEGIN DESCRIPTION:
Sweetwater Creek Trib2 25.0
END DESCRIPTION:
XS GIS Cut Line= 3
      1346954.99      6783088.00      1345174.96      6781467.91
      1345055.00      6780188.02
#Sta/Elev= 30
  2593.1 2582.67  2791.4 2582.63  2812.4 2583.55  2869.1 2583.18  2876.5 2584.29
  2883.3 2583.30  2925.9 2583.06  3209.0 2583.93  3824.5 2582.59  4121.9 2582.97
  4412.4 2579.99  4490.1 2577.68  4596.2 2577.30  4638.8 2575.75  4709.7 2575.67
  4752.3 2574.44  5051.7 2573.46  5052.1 2572.96  5056.6 2573.46  5210.8 2573.97
  5421.8 2577.55  5461.9 2577.26  5479.4 2578.43  5502.1 2577.98  5773.3 2583.70
  5823.5 2583.40  5883.8 2585.25  6034.4 2586.36  6104.7 2587.95  6285.5 2588.90
#Mann=3,-1,0
  2593.1    0.07       0  5051.7    0.07       0  5056.6    0.07       0
Bank Sta=5051.7,5056.6
Exp/Cntr=0.3,0.1

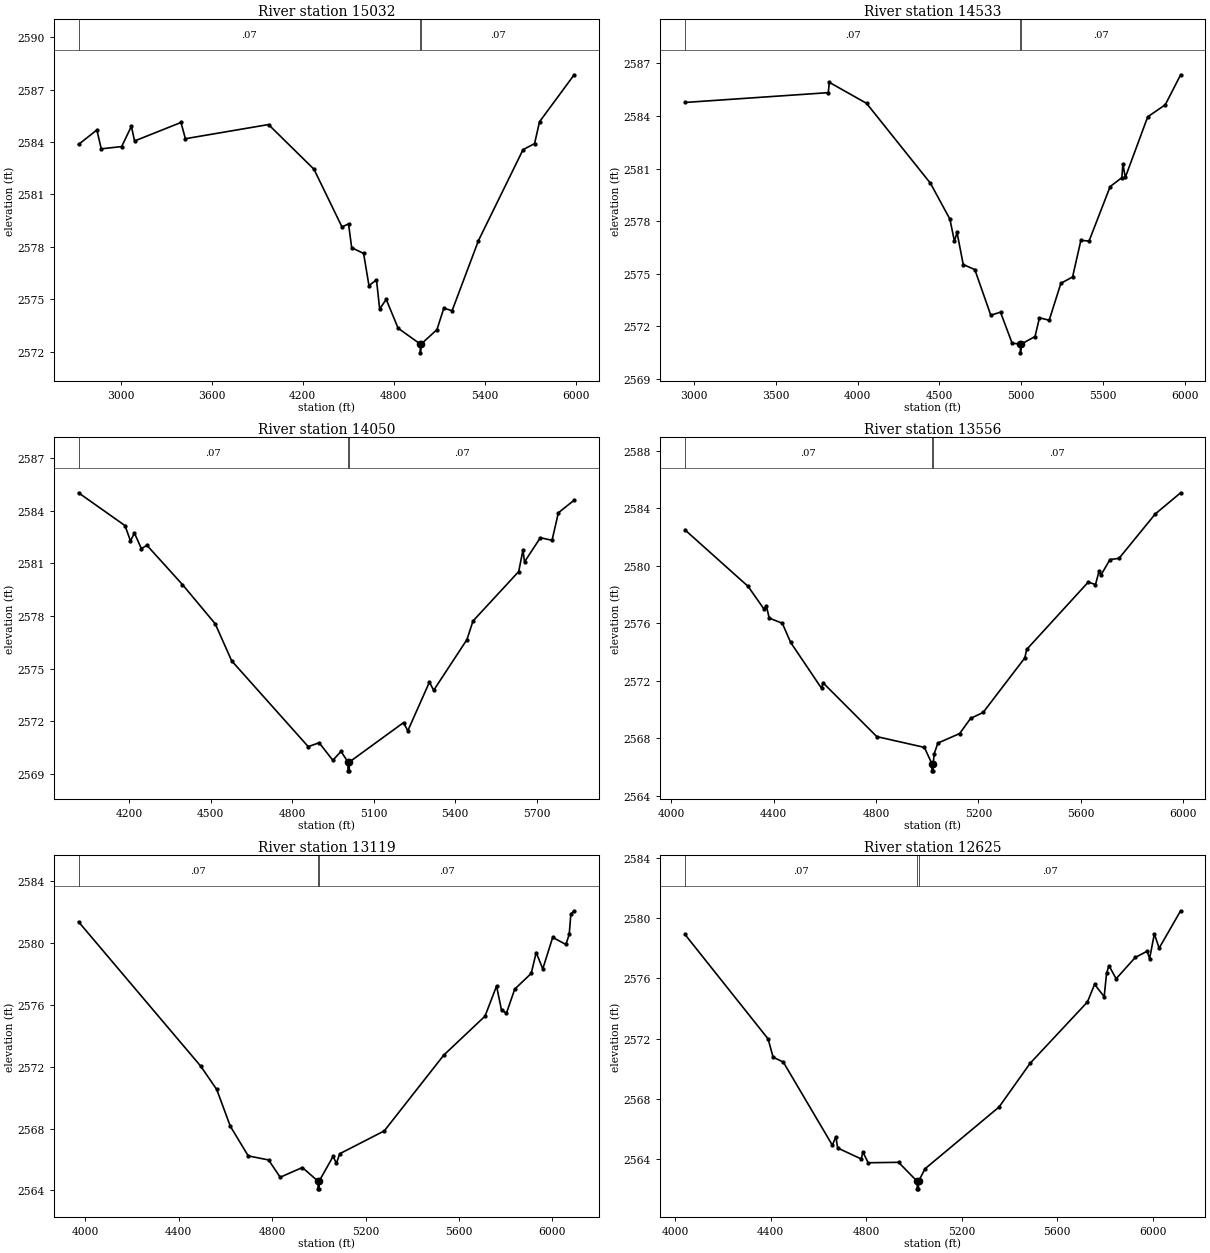
Type RM Length L Ch R = 1,15032,499,499,499
BEGIN DESCRIPTION:
Sweetwater Creek Trib2 24.0
END DESCRIPTION:
XS GIS Cut Line= 3
      1347005.00      6783037.99      1345595.33      6781248.80
      1345205.01      6780338.01
#Sta/Elev= 30
  2722.2 2583.86  2843.3 2584.69  2872.1 2583.61  3006.8 2583.74  3070.9 2584.90
  3091.8 2584.06  3398.0 2585.12  3426.9 2584.19  3975.3 2585.00  4275.2 2582.44
  4459.6 2579.14  4502.9 2579.31  4523.7 2577.95  4602.3 2577.62  4637.6 2575.78
  4687.3 2576.11  4708.2 2574.44  4751.4 2574.99  4830.0 2573.34  4976.6 2572.43
  4977.0 2571.93  4981.6 2572.43  5086.1 2573.26  5131.4 2574.49  5185.8 2574.34
  5359.9 2578.36  5653.6 2583.56  5729.8 2583.91  5762.4 2585.16  5990.9 2587.85
#Mann=3,-1,0
  2722.2    0.07       0  4976.6    0.07       0  4981.6    0.07       0
Bank Sta=4976.6,4981.6
Exp/Cntr=0.3,0.1

Type RM Length L Ch R = 1,14533,483,483,483
BEGIN DESCRIPTION:
Sweetwater Creek Trib2 23.0
END DESCRIPTION:
XS GIS Cut Line= 3
      1347055.01      6782938.02      1346060.54      6781138.53
      1345505.01      6780338.01
#Sta/Elev= 30
  2944.0 2584.77  3820.4 2585.33  3826.1 2585.92  4054.1 2584.72  4444.7 2580.16
  4563.8 2578.11  4591.3 2576.85  4607.4 2577.35  4645.2 2575.52  4716.2 2575.23
  4813.6 2572.63  4873.1 2572.80  4944.1 2571.03  4994.9 2570.98  4995.3 2570.48
  5000.0 2570.98  5084.2 2571.41  5111.2 2572.48  5170.7 2572.34  5242.3 2574.45
  5313.8 2574.81  5364.5 2576.90  5414.5 2576.86  5543.5 2579.97  5615.1 2580.48
  5621.4 2581.27  5636.0 2580.49  5773.1 2583.95  5880.5 2584.64  5974.4 2586.35
#Mann=3,-1,0
  2944.0    0.07       0  4994.9    0.07       0  5000.0    0.07       0
Bank Sta=4994.9,5000
Exp/Cntr=0.3,0.1

Type RM Length L Ch R = 1,14050,494,494,494
BEGIN DESCRIPTION:
Sweetwater Creek Trib2 22.0
END DESCRIPTION:
XS GIS Cut Line= 3
      1346605.00      6781987.97      1346485.04      6781008.09
      1346055.01      6780288.02
#Sta/Elev= 30
  4012.8 2585.03  4184.0 2583.16  4204.2 2582.29  4218.9 2582.73  4244.5 2581.84
  4264.6 2582.04  4395.6 2579.80  4516.5 2577.56  4577.0 2575.45  4859.0 2570.56
  4899.3 2570.78  4949.7 2569.78  4979.9 2570.29  5005.3 2569.68  5005.7 2569.18
  5010.1 2569.18  5010.4 2569.68  5210.2 2571.93  5225.8 2571.46  5305.6 2574.24
  5321.1 2573.77  5443.7 2576.66  5466.0 2577.72  5634.4 2580.54  5650.0 2581.76
  5655.8 2581.09  5714.2 2582.47  5757.2 2582.32  5780.5 2583.89  5838.7 2584.61
#Mann=3,-1,0
  4012.8    0.07       0  5005.3    0.07       0  5010.4    0.07       0
Bank Sta=5005.3,5010.4
Exp/Cntr=0.3,0.1

Type RM Length L Ch R = 1,13556,437,437,437
BEGIN DESCRIPTION:
Sweetwater Creek Trib2 21.0
END DESCRIPTION:
XS GIS Cut Line= 3
      1346704.99      6781788.03      1346924.80      6780867.51
      1346254.97      6780137.97
#Sta/Elev= 30
  4053.6 2582.50  4300.4 2578.57  4362.1 2577.00  4371.9 2577.21  4382.6 2576.37
  4434.0 2576.01  4466.3 2574.68  4587.5 2571.48  4592.6 2571.88  4803.1 2568.13
  4989.2 2567.38  5018.2 2566.25  5018.6 2565.75  5023.0 2565.75  5023.4 2566.25
  5027.6 2566.95  5041.8 2567.68  5126.8 2568.34  5169.4 2569.39  5218.7 2569.81
  5381.5 2573.60  5388.9 2574.19  5629.4 2578.87  5657.7 2578.70  5671.9 2579.64
  5678.7 2579.35  5714.4 2580.44  5749.6 2580.52  5891.4 2583.61  5990.4 2585.08
#Mann=3,-1,0
  4053.6    0.07       0  5018.2    0.07       0  5023.4    0.07       0
Bank Sta=5018.2,5023.4
Exp/Cntr=0.3,0.1

Type RM Length L Ch R = 1,13119,494,494,494
BEGIN DESCRIPTION:
Sweetwater Creek Trib2 20.0
END DESCRIPTION:
XS GIS Cut Line= 3
      1347004.99      6781788.03      1347328.50      6780810.90
      1346554.98      6780037.98
#Sta/Elev= 30
  3970.7 2581.38  4493.9 2572.04  4562.6 2570.53  4620.8 2568.15  4697.6 2566.23
  4784.6 2565.97  4834.5 2564.85  4929.3 2565.48  4996.3 2564.60  4996.7 2564.10
  5001.1 2564.10  5001.5 2564.60  5061.1 2566.20  5075.2 2565.75  5089.4 2566.37
  5280.3 2567.85  5534.9 2572.75  5711.6 2575.27  5761.1 2577.22  5782.3 2575.66
  5803.6 2575.47  5838.9 2577.02  5909.6 2578.04  5930.8 2579.39  5959.1 2578.33
  6001.5 2580.37  6058.1 2579.91  6072.3 2580.56  6079.3 2581.87  6093.5 2582.09
#Mann=3,-1,0
  3970.7    0.07       0  4996.3    0.07       0  5001.5    0.07       0
Bank Sta=4996.3,5001.5
Exp/Cntr=0.3,0.1

Type RM Length L Ch R = 1,12625,1491,1491,1491
BEGIN DESCRIPTION:
Sweetwater Creek Trib2 19.0
END DESCRIPTION:
XS GIS Cut Line= 3
      1347154.99      6781688.02      1347771.68      6780954.64
      1347755.00      6779837.97
#Sta/Elev= 30
  4041.8 2578.92  4389.7 2571.99  4410.6 2570.78  4453.5 2570.45  4659.0 2564.93
  4673.3 2565.50  4681.1 2564.75  4779.9 2564.02  4786.6 2564.49  4808.6 2563.77
  4936.0 2563.80  5013.7 2562.54  5014.2 2562.04  5019.1 2562.04  5019.6 2562.54
  5046.6 2563.37  5356.7 2567.47  5486.7 2570.37  5726.7 2574.44  5756.7 2575.61
  5796.7 2574.79  5806.7 2576.34  5816.7 2576.85  5846.7 2575.98  5926.7 2577.39
  5976.8 2577.81  5986.8 2577.31  6006.8 2578.96  6026.8 2578.01  6116.8 2580.49
#Mann=3,-1,0
  4041.8    0.07       0  5013.7    0.07       0  5019.6    0.07       0
Bank Sta=5013.7,5019.6
Exp/Cntr=0.3,0.1

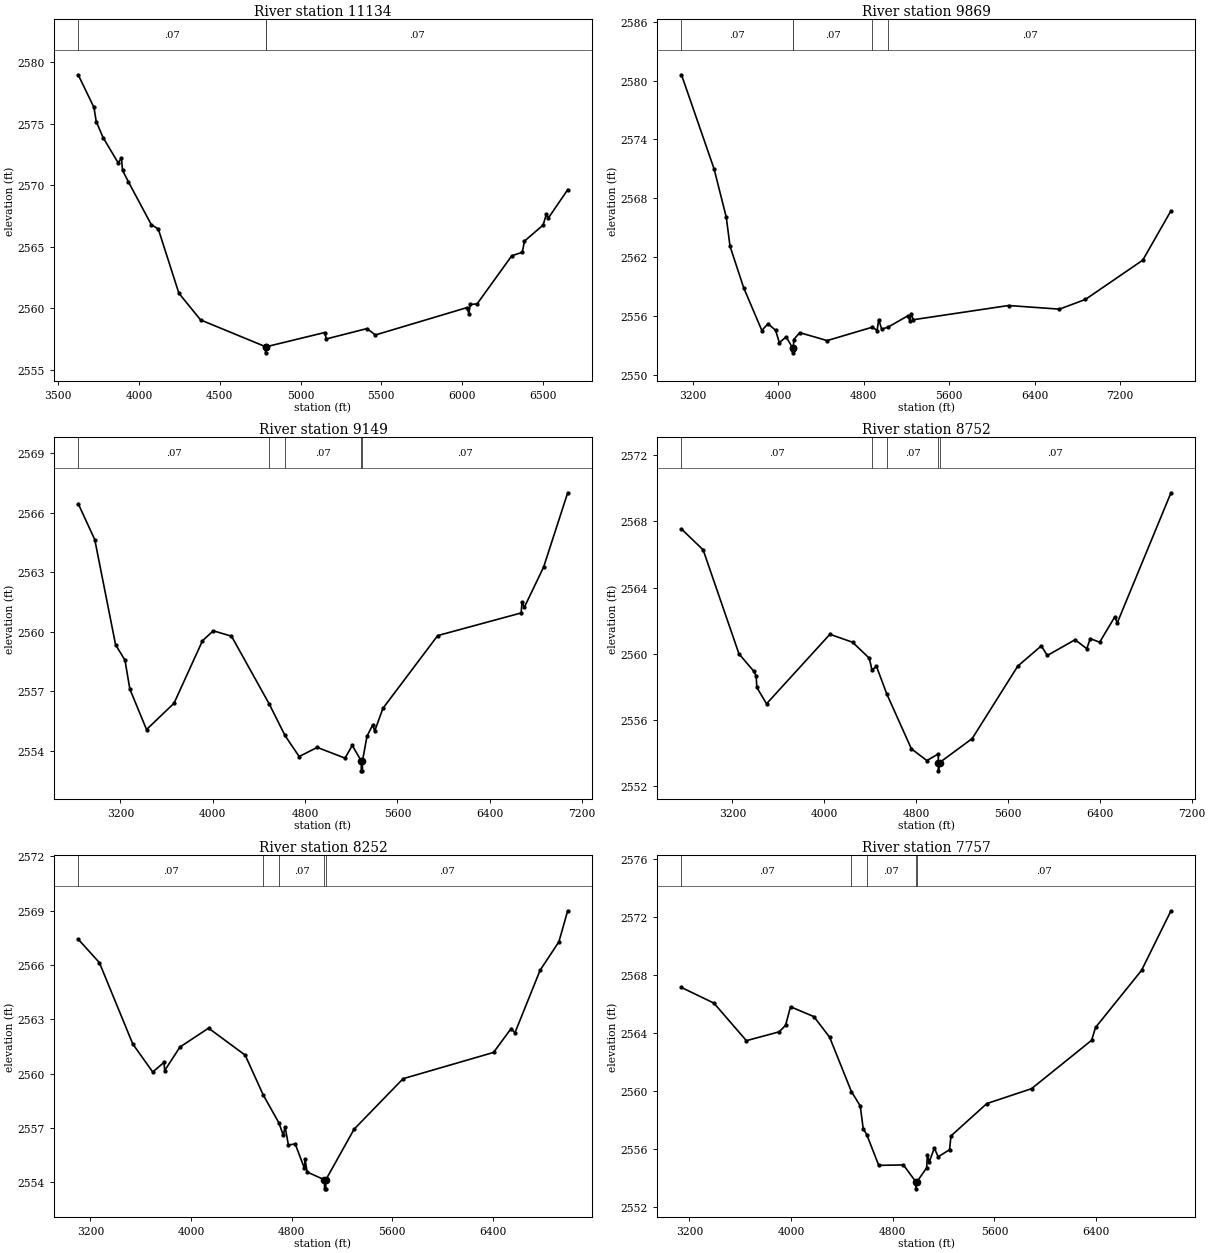
Type RM Length L Ch R = 1,11134,1265,1265,1265
BEGIN DESCRIPTION:
Sweetwater Creek Trib2 4166
END DESCRIPTION:
XS GIS Cut Line= 3
      1347694.86      6782775.10      1348748.87      6781890.72
      1348257.08      6780312.67
#Sta/Elev= 30
  3624.1 2578.97  3721.5 2576.32  3735.8 2575.17  3778.7 2573.86  3871.0 2571.83
  3891.9 2572.20  3898.4 2571.21  3934.8 2570.28  4076.6 2566.80  4119.5 2566.46
  4247.0 2561.24  4381.4 2559.07  4783.1 2556.90  4783.6 2556.40  4789.1 2556.90
  5149.5 2558.05  5159.5 2557.53  5411.3 2558.37  5462.6 2557.85  6029.3 2560.07
  6041.6 2559.58  6050.3 2560.33  6092.2 2560.37  6306.9 2564.28  6372.0 2564.56
  6385.5 2565.47  6500.7 2566.77  6521.6 2567.68  6532.1 2567.32  6652.9 2569.64
#Mann=3,-1,0
  3624.1    0.07       0  4783.1    0.07       0  4789.1    0.07       0
Bank Sta=4783.1,4789.1
Exp/Cntr=0.3,0.1

Type RM Length L Ch R = 1,9869,720,720,720
BEGIN DESCRIPTION:
Sweetwater Creek Trib2 18.0
END DESCRIPTION:
XS GIS Cut Line= 3
      1348155.02      6784287.98      1349389.81      6782838.53
      1348971.43      6780197.47
#Sta/Elev= 30
  3095.9 2580.60  3400.6 2571.00  3514.8 2566.06  3549.9 2563.10  3677.3 2558.87
  3847.5 2554.50  3904.6 2555.19  3976.0 2554.52  4011.1 2553.26  4074.8 2553.85
  4135.1 2552.72  4135.6 2552.22  4141.9 2552.72  4146.2 2553.58  4202.2 2554.28
  4458.0 2553.47  4881.5 2554.84  4925.8 2554.50  4940.1 2555.61  4968.7 2554.64
  5027.5 2554.84  5213.2 2556.00  5233.4 2555.45  5243.5 2556.23  5263.8 2555.60
  6154.8 2557.05  6630.6 2556.68  6873.6 2557.67  7410.2 2561.68  7674.0 2566.72
#Mann=5,-1,0
  3095.9    0.07       0  4135.1   0.035       0  4141.9    0.07       0
  4881.5   0.035       0  5027.5    0.07       0
Bank Sta=4135.1,4141.9
Exp/Cntr=0.3,0.1

Type RM Length L Ch R = 1,9149,397,397,397
BEGIN DESCRIPTION:
Sweetwater Creek Trib2 17.0
END DESCRIPTION:
XS GIS Cut Line= 3
      1351155.01      6784288.02      1349964.99      6782477.98
      1350555.00      6780488.00
#Sta/Elev= 30
  2833.8 2566.45  2977.4 2564.64  3157.7 2559.35  3239.1 2558.57  3281.2 2557.12
  3425.8 2555.08  3663.8 2556.40  3910.9 2559.55  4004.3 2560.05  4162.2 2559.78
  4488.8 2556.37  4625.8 2554.78  4748.5 2553.72  4905.0 2554.18  5146.0 2553.64
  5208.6 2554.28  5286.6 2553.50  5287.1 2553.00  5296.9 2553.00  5297.4 2553.50
  5336.6 2554.75  5385.9 2555.31  5403.1 2555.00  5474.8 2556.15  5949.1 2559.81
  6672.5 2560.95  6679.2 2561.48  6700.1 2561.24  6867.0 2563.26  7075.6 2567.00
#Mann=5,-1,0
  2833.8    0.07       0  4488.8   0.035       0  4625.8    0.07       0
  5286.6    0.07       0  5297.4    0.07       0
Bank Sta=5286.6,5297.4
Exp/Cntr=0.3,0.1

Type RM Length L Ch R = 1,8752,500,500,500
BEGIN DESCRIPTION:
Sweetwater Creek Trib2 16.0
END DESCRIPTION:
XS GIS Cut Line= 3
      1351305.00      6784387.99      1350321.76      6782370.64
      1350704.99      6780388.04
#Sta/Elev= 30
  2755.8 2567.54  2944.6 2566.28  3256.4 2560.00  3383.9 2558.96  3406.4 2558.67
  3412.1 2557.97  3496.6 2556.98  4048.6 2561.18  4245.9 2560.70  4392.2 2559.73
  4414.8 2559.02  4454.3 2559.24  4543.7 2557.58  4758.4 2554.26  4893.6 2553.55
  4991.8 2553.95  4993.3 2553.43  4993.8 2552.93  5004.1 2553.43  5287.9 2554.88
  5685.1 2559.26  5890.2 2560.48  5942.0 2559.90  6184.2 2560.85  6286.0 2560.31
  6316.6 2560.92  6398.1 2560.70  6530.5 2562.24  6550.8 2561.86  7019.3 2569.73
#Mann=5,-1,0
  2755.8    0.07       0  4414.8   0.035       0  4543.7    0.07       0
  4993.3    0.07       0  5004.1    0.07       0
Bank Sta=4993.3,5004.1
Exp/Cntr=0.3,0.1

Type RM Length L Ch R = 1,8252,495,495,495
BEGIN DESCRIPTION:
Sweetwater Creek Trib2 15.0
END DESCRIPTION:
XS GIS Cut Line= 3
      1351354.99      6784287.97      1350760.94      6782485.75
      1350755.00      6780487.96
#Sta/Elev= 30
  3102.4 2567.42  3270.8 2566.13  3536.5 2561.64  3695.3 2560.09  3785.3 2560.62
  3790.6 2560.17  3912.4 2561.47  4140.0 2562.51  4431.2 2561.02  4575.7 2558.81
  4699.1 2557.29  4734.4 2556.60  4748.8 2557.05  4775.3 2556.06  4829.2 2556.12
  4902.4 2554.78  4907.7 2555.29  4923.9 2554.57  5062.3 2554.14  5062.8 2553.64
  5072.7 2553.64  5073.2 2554.14  5297.7 2556.93  5687.8 2559.72  6407.8 2561.17
  6547.8 2562.49  6577.8 2562.25  6777.8 2565.70  6927.8 2567.28  6997.8 2568.99
#Mann=5,-1,0
  3102.4    0.07       0  4575.7   0.035       0  4699.1    0.07       0
  5062.3    0.07       0  5073.2    0.07       0
Bank Sta=5062.3,5073.2
Exp/Cntr=0.3,0.1

Type RM Length L Ch R = 1,7757,479,479,479
BEGIN DESCRIPTION:
Sweetwater Creek Trib2 14.0
END DESCRIPTION:
XS GIS Cut Line= 3
      1351555.00      6784188.02      1351178.18      6782364.04
      1350955.00      6780388.01
#Sta/Elev= 30
  3137.5 2567.14  3392.8 2566.06  3648.1 2563.47  3906.0 2564.08  3956.3 2564.53
  3995.3 2565.81  4179.1 2565.13  4302.9 2563.71  4474.3 2559.96  4543.9 2558.97
  4567.1 2557.41  4595.5 2556.98  4689.5 2554.87  4883.6 2554.90  4980.2 2553.75
  4980.7 2553.25  4991.2 2553.75  5066.5 2554.70  5072.2 2555.61  5086.6 2555.10
  5126.8 2556.06  5157.0 2555.46  5246.8 2555.95  5257.7 2556.90  5539.5 2559.13
  5891.7 2560.16  6364.7 2563.50  6394.9 2564.38  6757.1 2568.32  6988.6 2572.43
#Mann=5,-1,0
  3137.5    0.07       0  4474.3   0.035       0  4595.5    0.07       0
  4980.2    0.07       0  4991.2    0.07       0
Bank Sta=4980.2,4991.2
Exp/Cntr=0.3,0.1

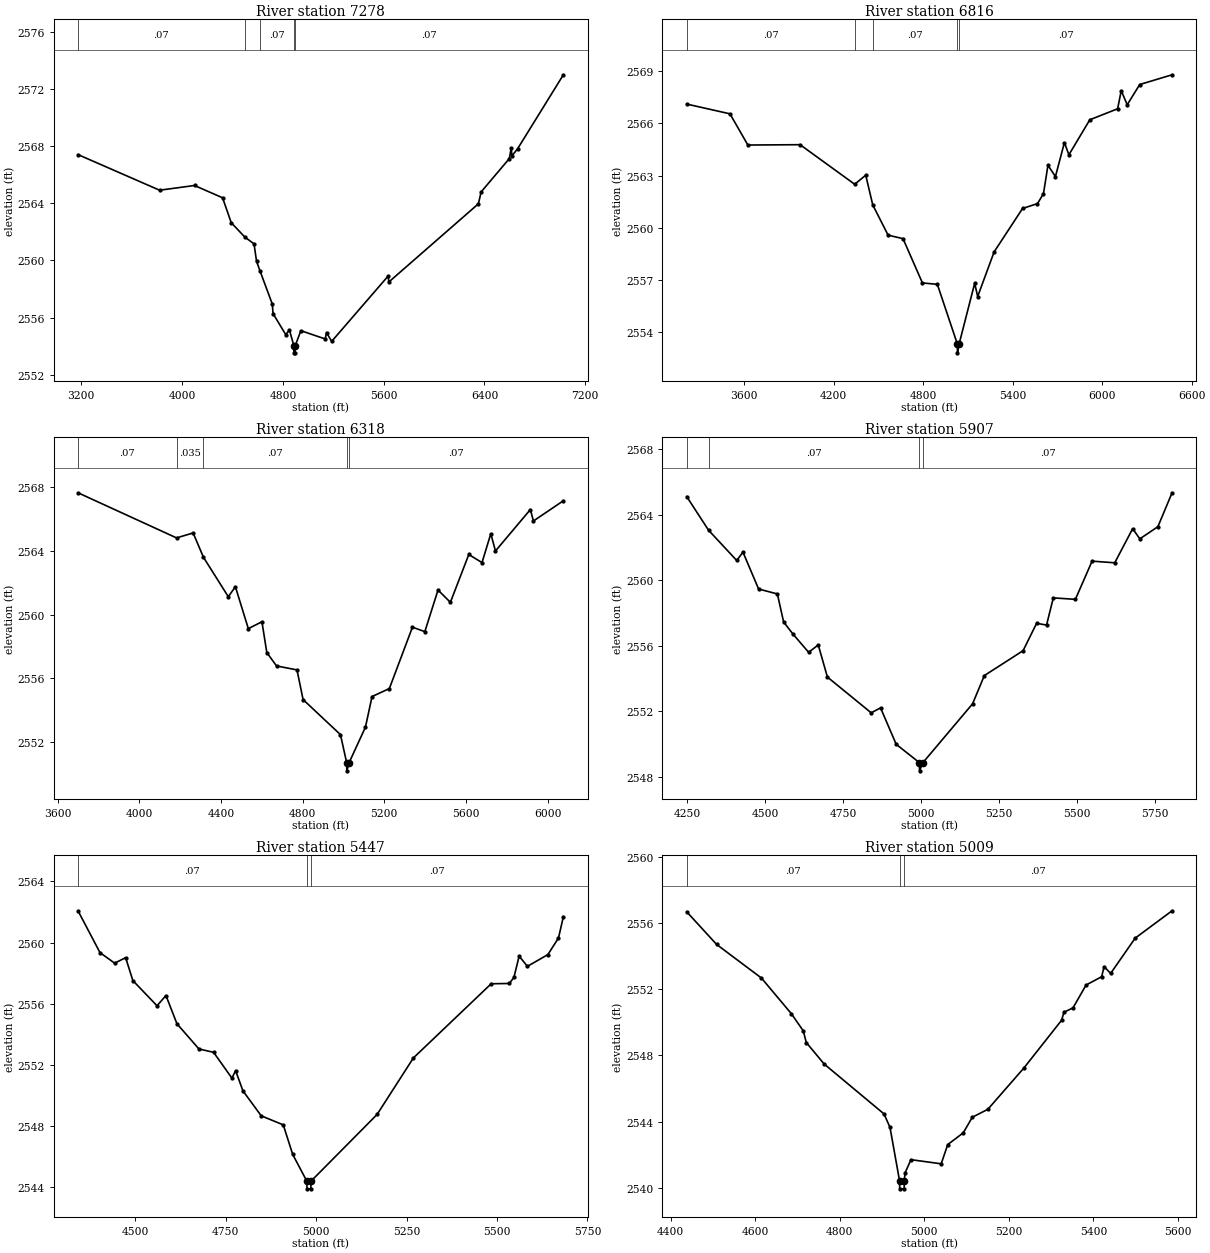
Type RM Length L Ch R = 1,7278,462,462,462
BEGIN DESCRIPTION:
Sweetwater Creek Trib2 13.0
END DESCRIPTION:
XS GIS Cut Line= 3
      1351755.00      6784188.03      1351571.48      6782371.07
      1351155.01      6780388.03
#Sta/Elev= 30
  3173.8 2567.40  3821.4 2564.91  4098.5 2565.24  4321.4 2564.38  4390.0 2562.64
  4498.2 2561.63  4570.9 2561.16  4591.0 2559.94  4618.8 2559.26  4716.4 2556.94
  4721.7 2556.29  4822.2 2554.82  4852.3 2555.13  4887.0 2554.04  4887.5 2553.54
  4897.6 2553.54  4898.1 2554.04  4942.8 2555.09  5136.0 2554.51  5146.2 2554.96
  5187.1 2554.34  5635.6 2558.91  5640.7 2558.49  6351.9 2563.96  6373.5 2564.79
  6597.2 2567.12  6612.6 2567.87  6617.7 2567.31  6662.5 2567.80  7026.3 2572.98
#Mann=5,-1,0
  3173.8    0.07       0  4498.2   0.035       0  4618.8    0.07       0
  4887.0    0.07       0  4898.1    0.07       0
Bank Sta=4887,4898.1
Exp/Cntr=0.3,0.1

Type RM Length L Ch R = 1,6816,498,498,498
BEGIN DESCRIPTION:
Sweetwater Creek Trib2 12.0
END DESCRIPTION:
XS GIS Cut Line= 3
      1351955.00      6783987.98      1351955.84      6782203.28
      1351855.00      6780738.05
#Sta/Elev= 30
  3215.3 2567.10  3505.3 2566.54  3625.3 2564.75  3975.3 2564.77  4341.4 2562.50
  4415.3 2563.02  4462.6 2561.31  4565.3 2559.58  4665.3 2559.38  4795.3 2556.84
  4895.3 2556.76  5029.7 2553.33  5030.2 2552.83  5041.0 2553.33  5145.6 2556.82
  5165.7 2556.06  5275.9 2558.62  5466.4 2561.11  5566.6 2561.39  5606.7 2561.96
  5636.8 2563.59  5686.9 2562.94  5747.0 2564.89  5777.1 2564.19  5917.4 2566.20
  6103.8 2566.83  6127.9 2567.87  6168.0 2567.06  6251.8 2568.22  6468.7 2568.78
#Mann=5,-1,0
  3215.3    0.07       0  4341.4   0.035       0  4462.6    0.07       0
  5029.7    0.07       0  5041.0    0.07       0
Bank Sta=5029.7,5041
Exp/Cntr=0.3,0.1

Type RM Length L Ch R = 1,6318,411,411,411
BEGIN DESCRIPTION:
Sweetwater Creek Trib2 11.0
END DESCRIPTION:
XS GIS Cut Line= 3
      1352904.99      6783287.98      1352405.03      6782088.08
      1352005.01      6781088.01
#Sta/Elev= 30
  3700.1 2567.64  4182.7 2564.81  4264.0 2565.12  4314.7 2563.59  4436.2 2561.12
  4470.9 2561.75  4534.2 2559.12  4600.9 2559.55  4624.7 2557.62  4672.4 2556.78
  4772.6 2556.53  4802.4 2554.67  4985.5 2552.47  5016.0 2550.70  5016.5 2550.20
  5027.3 2550.70  5107.8 2552.94  5140.1 2554.86  5224.9 2555.36  5338.0 2559.21
  5398.6 2558.93  5463.2 2561.54  5523.8 2560.77  5614.0 2563.77  5678.6 2563.26
  5721.7 2565.07  5744.6 2563.99  5915.6 2566.59  5930.4 2565.87  6077.1 2567.14
#Mann=5,-1,0
  3700.1    0.07       0  4182.7   0.035       0  4314.7    0.07       0
  5016.0    0.07       0  5027.3    0.07       0
Bank Sta=5016,5027.3
Exp/Cntr=0.3,0.1

Type RM Length L Ch R = 1,5907,460,460,460
BEGIN DESCRIPTION:
Sweetwater Creek Trib2 10.0
END DESCRIPTION:
XS GIS Cut Line= 3
      1352755.00      6782787.99      1352800.03      6782037.94
      1352405.01      6781338.02
#Sta/Elev= 30
  4248.6 2565.11  4318.5 2563.06  4408.9 2561.21  4428.9 2561.72  4479.0 2559.47
  4539.1 2559.17  4559.1 2557.46  4589.2 2556.72  4639.3 2555.61  4670.1 2556.06
  4699.4 2554.10  4839.7 2551.92  4869.7 2552.22  4919.8 2550.00  4994.1 2548.88
  4994.6 2548.38  5005.4 2548.88  5164.6 2552.47  5202.2 2554.19  5326.4 2555.71
  5369.7 2557.38  5401.5 2557.27  5423.2 2558.93  5493.9 2558.84  5547.4 2561.17
  5620.0 2561.07  5677.4 2563.15  5700.4 2562.53  5758.2 2563.27  5803.7 2565.34
#Mann=4,-1,0
  4248.6   0.035       0  4318.5    0.07       0  4994.1    0.07       0
  5005.4    0.07       0
Bank Sta=4994.1,5005.4
Exp/Cntr=0.3,0.1

Type RM Length L Ch R = 1,5447,438,438,438
BEGIN DESCRIPTION:
Sweetwater Creek Trib2 9.0
END DESCRIPTION:
XS GIS Cut Line= 3
      1353105.00      6782637.98      1353210.18      6781988.44
      1352804.99      6781437.99
#Sta/Elev= 30
  4342.0 2562.08  4402.8 2559.34  4443.3 2558.65  4473.7 2559.01  4493.6 2557.51
  4560.4 2555.86  4585.1 2556.53  4615.5 2554.68  4676.3 2553.03  4716.8 2552.81
  4767.4 2551.12  4777.6 2551.61  4797.8 2550.29  4848.5 2548.65  4909.3 2548.06
  4935.5 2546.12  4974.5 2544.37  4975.0 2543.87  4985.4 2543.87  4985.9 2544.37
  5168.6 2548.74  5268.9 2552.44  5484.0 2557.30  5534.2 2557.32  5546.9 2557.72
  5561.2 2559.11  5584.1 2558.44  5640.7 2559.21  5670.0 2560.30  5683.5 2561.69
#Mann=3,-1,0
  4342.0    0.07       0  4974.5    0.07       0  4985.9    0.07       0
Bank Sta=4974.5,4985.9
Exp/Cntr=0.3,0.1

Type RM Length L Ch R = 1,5009,492,492,492
BEGIN DESCRIPTION:
Sweetwater Creek Trib2 8.0
END DESCRIPTION:
XS GIS Cut Line= 3
      1353954.99      6782187.99      1353555.43      6781793.21
      1353054.97      6781487.98
#Sta/Elev= 30
  4438.3 2556.67  4509.0 2554.70  4615.1 2552.67  4685.8 2550.52  4714.1 2549.48
  4721.1 2548.78  4763.5 2547.48  4905.0 2544.47  4919.1 2543.66  4941.6 2540.45
  4942.1 2539.95  4952.6 2539.95  4953.1 2540.45  4954.5 2540.90  4968.7 2541.71
  5040.2 2541.46  5055.6 2542.62  5092.4 2543.33  5113.7 2544.27  5150.5 2544.75
  5235.7 2547.24  5324.8 2550.12  5330.6 2550.61  5351.9 2550.87  5382.8 2552.25
  5419.6 2552.75  5425.5 2553.36  5440.9 2552.95  5499.0 2555.08  5586.2 2556.73
#Mann=3,-1,0
  4438.3    0.07       0  4941.6    0.07       0  4953.1    0.07       0
Bank Sta=4941.6,4953.1
Exp/Cntr=0.3,0.1

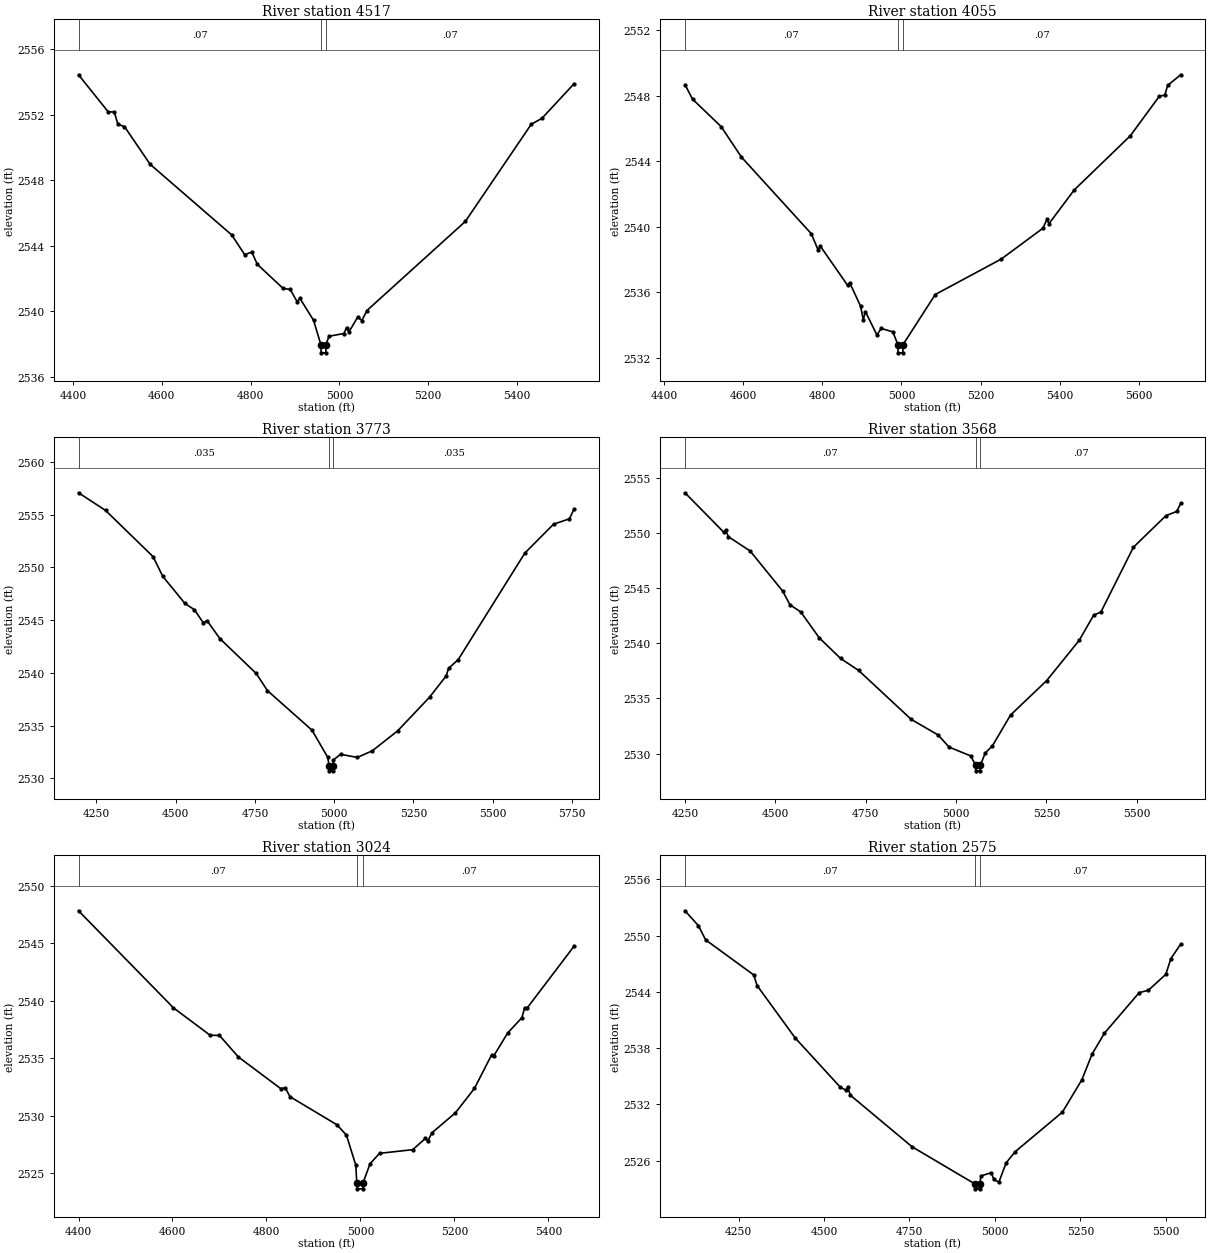
Type RM Length L Ch R = 1,4517,462,462,462
BEGIN DESCRIPTION:
Sweetwater Creek Trib2 7.0
END DESCRIPTION:
XS GIS Cut Line= 3
      1354105.01      6781988.02      1353814.74      6781477.46
      1353304.98      6781337.99
#Sta/Elev= 30
  4412.7 2554.44  4479.8 2552.17  4493.2 2552.18  4501.4 2551.41  4516.2 2551.28
  4573.8 2548.98  4757.8 2544.66  4786.8 2543.46  4802.7 2543.62  4815.3 2542.87
  4873.3 2541.40  4889.2 2541.34  4905.0 2540.58  4910.8 2540.81  4941.9 2539.45
  4958.3 2537.97  4958.8 2537.47  4969.4 2537.47  4969.9 2537.97  4976.4 2538.48
  5010.1 2538.65  5016.1 2539.01  5021.3 2538.74  5041.2 2539.65  5050.6 2539.44
  5061.9 2540.05  5283.5 2545.49  5431.9 2551.42  5455.9 2551.78  5528.5 2553.90
#Mann=3,-1,0
  4412.7    0.07       0  4958.3    0.07       0  4969.9    0.07       0
Bank Sta=4958.3,4969.9
Exp/Cntr=0.3,0.1

Type RM Length L Ch R = 1,4055,282,282,282
BEGIN DESCRIPTION:
Sweetwater Creek Trib2 4165
END DESCRIPTION:
XS GIS Cut Line= 3
      1354298.40      6781736.51      1354155.37      6781208.12
      1353483.80      6780990.03
#Sta/Elev= 30
  4452.6 2548.68  4471.8 2547.79  4544.3 2546.11  4595.2 2544.26  4772.2 2539.57
  4789.3 2538.58  4794.5 2538.83  4863.9 2536.42  4869.0 2536.59  4896.5 2535.16
  4903.7 2534.32  4908.9 2534.82  4938.0 2533.39  4948.8 2533.79  4978.3 2533.58
  4991.0 2532.80  4991.5 2532.30  5003.5 2532.30  5004.0 2532.80  5085.5 2535.86
  5252.7 2538.03  5357.9 2539.91  5367.9 2540.45  5373.2 2540.19  5437.1 2542.25
  5578.7 2545.55  5652.3 2547.97  5666.1 2548.04  5673.3 2548.63  5706.1 2549.28
#Mann=3,-1,0
  4452.6    0.07       0  4991.0    0.07       0  5004.0    0.07       0
Bank Sta=4991,5004
Exp/Cntr=0.3,0.1

Type RM Length L Ch R = 1,3773,205,205,205
BEGIN DESCRIPTION:
Sweetwater Creek Trib2 6.0
END DESCRIPTION:
XS GIS Cut Line= 3
      1354473.94      6781992.99      1354425.07      6781188.18
      1354370.87      6780433.02
#Sta/Elev= 30
  4193.7 2557.07  4278.9 2555.40  4429.1 2551.01  4459.2 2549.16  4529.3 2546.58
  4559.4 2545.98  4586.6 2544.77  4599.4 2544.94  4639.5 2543.25  4754.2 2539.94
  4789.8 2538.31  4930.0 2534.57  4980.1 2531.98  4983.7 2531.21  4984.2 2530.71
  4996.2 2530.71  4996.7 2531.21  4997.6 2531.74  5020.2 2532.28  5073.1 2531.98
  5120.5 2532.61  5200.7 2534.51  5300.9 2537.69  5353.1 2539.70  5361.1 2540.43
  5391.2 2541.25  5601.7 2551.36  5692.0 2554.09  5742.1 2554.60  5757.1 2555.54
#Mann=3,-1,0
  4193.7   0.035       0  4983.7   0.035       0  4996.7   0.035       0
Bank Sta=4983.7,4996.7
Exp/Cntr=0.3,0.1

Type RM Length L Ch R = 1,3568,544,544,544
BEGIN DESCRIPTION:
Sweetwater Creek Trib2 5.0
END DESCRIPTION:
XS GIS Cut Line= 3
      1354624.23      6781848.14      1354595.21      6781098.50
      1354583.60      6780477.41
#Sta/Elev= 30
  4249.8 2553.62  4357.1 2550.05  4362.1 2550.24  4370.0 2549.64  4430.1 2548.35
  4520.1 2544.72  4540.2 2543.48  4570.2 2542.83  4621.4 2540.48  4680.3 2538.62
  4730.3 2537.53  4875.8 2533.10  4950.5 2531.68  4980.5 2530.59  5040.5 2529.79
  5054.0 2528.94  5054.5 2528.44  5066.6 2528.44  5067.1 2528.94  5080.5 2530.05
  5100.5 2530.71  5150.5 2533.49  5250.5 2536.61  5340.6 2540.26  5380.6 2542.54
  5400.6 2542.82  5490.6 2548.69  5580.6 2551.55  5610.6 2551.93  5621.2 2552.65
#Mann=3,-1,0
  4249.8    0.07       0  5054.0    0.07       0  5067.1    0.07       0
Bank Sta=5054,5067.1
Exp/Cntr=0.3,0.1

Type RM Length L Ch R = 1,3024,449,449,449
BEGIN DESCRIPTION:
Sweetwater Creek Trib2 4.0
END DESCRIPTION:
XS GIS Cut Line= 3
      1355105.00      6781637.95      1355120.06      6781038.14
      1355055.00      6780588.02
#Sta/Elev= 30
  4400.0 2547.83  4602.1 2539.38  4680.0 2537.00  4700.0 2536.98  4740.1 2535.11
  4830.1 2532.36  4840.1 2532.41  4850.1 2531.65  4950.1 2529.20  4970.1 2528.31
  4990.1 2525.69  4992.2 2524.13  4992.7 2523.63  5004.8 2523.63  5005.3 2524.13
  5020.4 2525.81  5040.6 2526.72  5111.3 2527.04  5138.4 2528.03  5143.5 2527.78
  5151.7 2528.49  5202.2 2530.25  5242.6 2532.37  5279.0 2535.28  5284.1 2535.23
  5313.4 2537.20  5343.7 2538.53  5349.3 2539.39  5354.4 2539.35  5454.8 2544.76
#Mann=3,-1,0
  4400.0    0.07       0  4992.2    0.07       0  5005.3    0.07       0
Bank Sta=4992.2,5005.3
Exp/Cntr=0.3,0.1

Type RM Length L Ch R = 1,2575,983,983,983
BEGIN DESCRIPTION:
Sweetwater Creek Trib2 3.0
END DESCRIPTION:
XS GIS Cut Line= 3
      1355355.00      6781788.00      1355460.20      6780887.52
      1355155.02      6780438.03
#Sta/Elev= 30
  4093.4 2552.65  4132.6 2551.07  4153.8 2549.55  4294.8 2545.80  4304.3 2544.68
  4415.6 2539.10  4546.5 2533.89  4564.5 2533.50  4569.5 2533.89  4576.7 2533.00
  4757.9 2527.48  4942.6 2523.50  4943.1 2523.00  4955.3 2523.00  4955.8 2523.50
  4959.2 2524.37  4989.5 2524.73  4996.4 2524.03  5011.5 2523.70  5032.8 2525.77
  5059.9 2526.98  5197.5 2531.18  5254.4 2534.63  5284.3 2537.37  5320.3 2539.59
  5422.0 2543.92  5449.1 2544.18  5499.9 2545.87  5514.9 2547.56  5543.3 2549.08
#Mann=3,-1,0
  4093.4    0.07       0  4942.6    0.07       0  4955.8    0.07       0
Bank Sta=4942.6,4955.8
Exp/Cntr=0.3,0.1