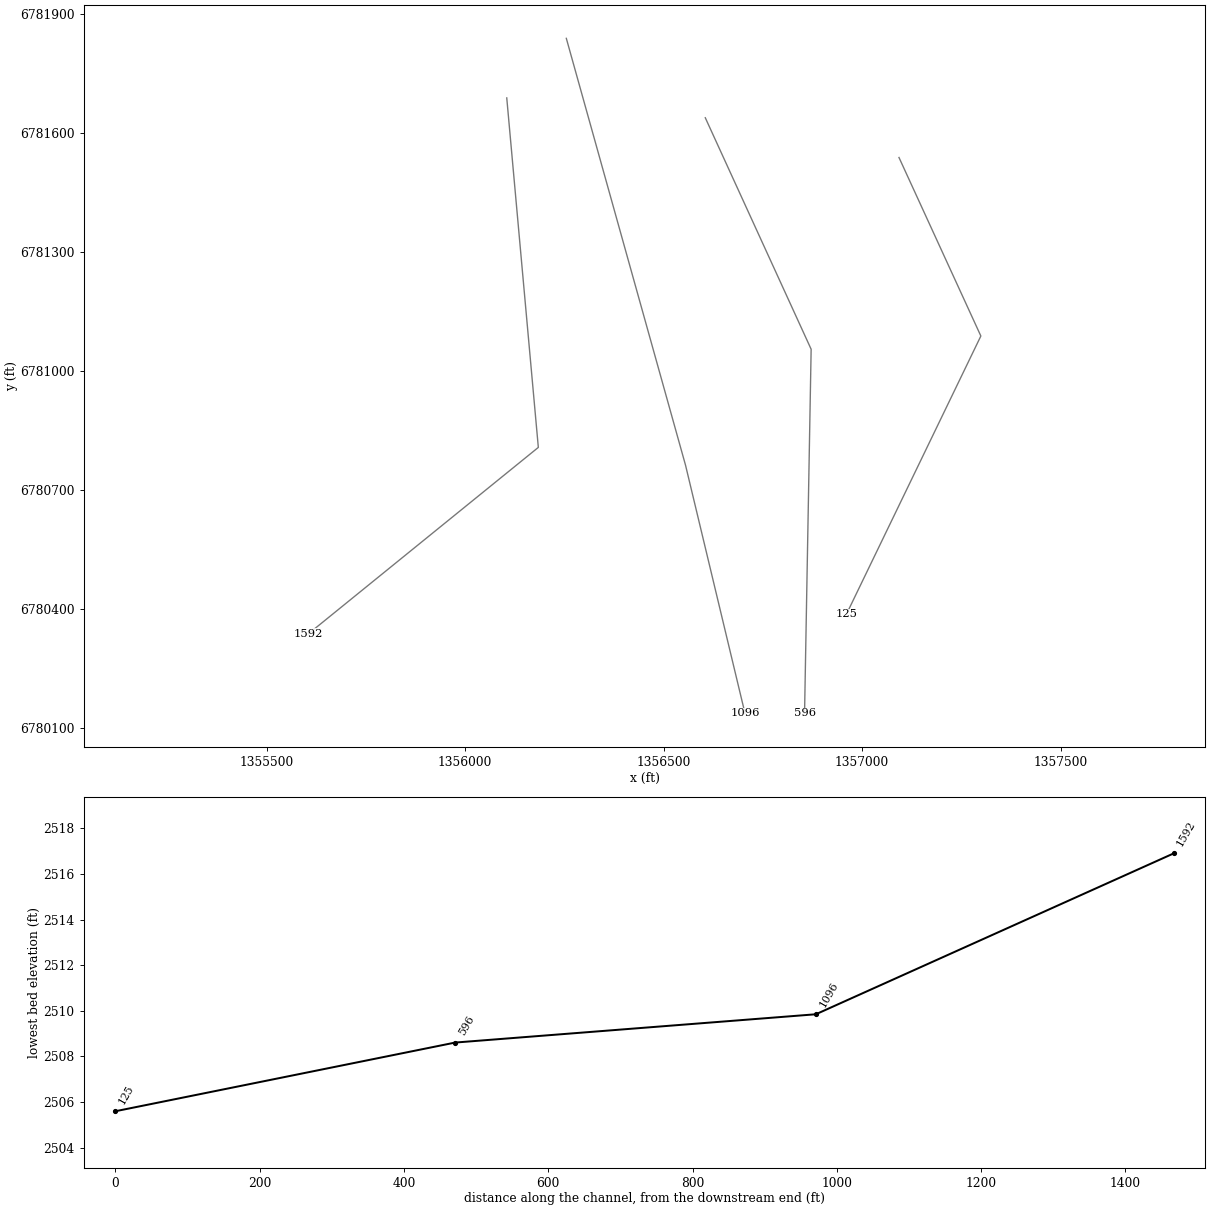
HEC-RAS study Sweetwater Creek Trib2.prj: Sweetwater Creek Trib2 Base Level Engineering

--- Sweetwater Creek Trib2.g01 (geometry) --- (continued)

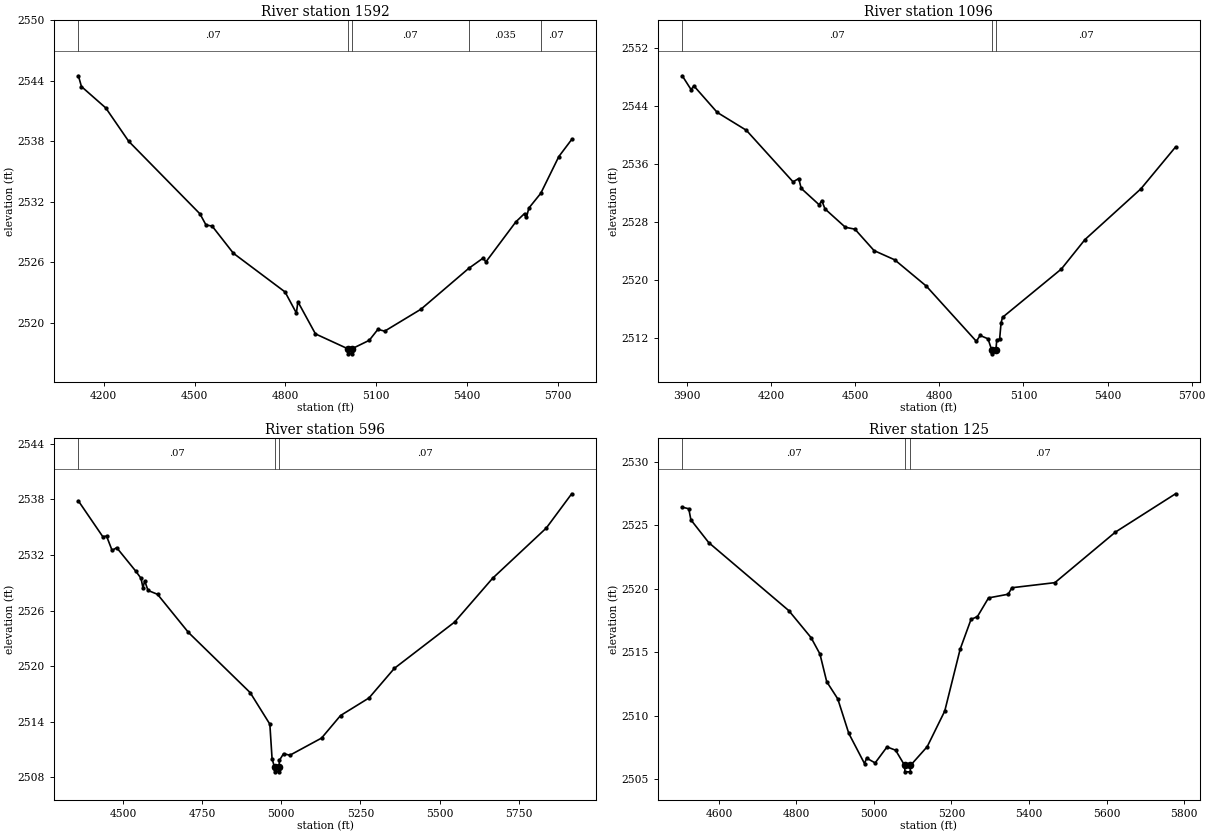
Type RM Length L Ch R = 1,1592,496,496,496
BEGIN DESCRIPTION:
Sweetwater Creek Trib2 2.0
END DESCRIPTION:
XS GIS Cut Line= 3
      1356105.00      6781688.01      1356184.52      6780807.80
      1355605.02      6780338.01
#Sta/Elev= 30
  4116.2 2544.49  4126.3 2543.42  4206.6 2541.30  4282.4 2537.99  4517.8 2530.79
  4537.9 2529.68  4558.0 2529.58  4628.3 2526.88  4799.0 2523.04  4836.4 2520.95
  4841.4 2522.07  4899.4 2518.88  5006.6 2517.40  5007.1 2516.90  5019.3 2516.90
  5019.8 2517.40  5077.1 2518.24  5105.8 2519.33  5128.1 2519.15  5248.1 2521.33
  5405.8 2525.38  5454.3 2526.42  5462.3 2526.01  5561.4 2529.99  5590.1 2530.82
  5596.6 2530.44  5604.4 2531.36  5643.9 2532.83  5703.6 2536.48  5746.0 2538.17
#Mann=5,-1,0
  4116.2    0.07       0  5006.6    0.07       0  5019.8    0.07       0
  5405.8   0.035       0  5643.9    0.07       0
Bank Sta=5006.6,5019.8
Exp/Cntr=0.3,0.1

Type RM Length L Ch R = 1,1096,500,500,500
BEGIN DESCRIPTION:
Sweetwater Creek Trib2 1.0
END DESCRIPTION:
XS GIS Cut Line= 3
      1356254.99      6781838.04      1356555.27      6780762.88
      1356705.01      6780137.97
#Sta/Elev= 30
  3883.7 2548.12  3914.9 2546.23  3925.3 2546.72  4008.3 2543.08  4112.2 2540.62
  4278.8 2533.52  4299.0 2533.98  4307.7 2532.63  4371.7 2530.37  4381.3 2530.94
  4392.5 2529.80  4465.2 2527.27  4499.3 2527.01  4567.6 2524.06  4641.2 2522.79
  4754.0 2519.17  4932.4 2511.57  4945.6 2512.38  4973.9 2511.92  4987.3 2510.35
  4987.8 2509.85  5002.0 2510.35  5005.1 2511.77  5015.2 2511.83  5020.4 2514.10
  5025.6 2514.87  5235.6 2521.53  5319.7 2525.58  5519.2 2532.57  5642.6 2538.32
#Mann=3,-1,0
  3883.7    0.07       0  4987.3    0.07       0  5002.0    0.07       0
Bank Sta=4987.3,5002
Exp/Cntr=0.3,0.1

Type RM Length L Ch R = 1,596,471,471,471
BEGIN DESCRIPTION:
Sweetwater Creek Trib2 0.1
END DESCRIPTION:
XS GIS Cut Line= 3
      1356604.98      6781638.04      1356871.60      6781055.01
      1356855.00      6780137.96
#Sta/Elev= 30
  4358.9 2537.82  4435.9 2533.97  4447.8 2534.03  4465.3 2532.49  4479.9 2532.78
  4539.8 2530.26  4556.9 2529.47  4562.8 2528.45  4568.3 2529.20  4578.9 2528.17
  4608.9 2527.75  4706.5 2523.64  4901.6 2517.15  4963.7 2513.75  4970.7 2510.03
  4978.4 2509.11  4978.9 2508.61  4992.6 2508.61  4993.1 2509.11  4993.7 2509.84
  5007.0 2510.57  5027.0 2510.40  5127.0 2512.25  5187.0 2514.68  5277.1 2516.58
  5357.1 2519.77  5547.1 2524.75  5667.1 2529.47  5837.1 2534.90  5917.2 2538.59
#Mann=3,-1,0
  4358.9    0.07       0  4978.4    0.07       0  4993.1    0.07       0
Bank Sta=4978.4,4993.1
Exp/Cntr=0.3,0.1

Type RM Length L Ch R = 1,125,0,0,0
BEGIN DESCRIPTION:
Sweetwater Creek Trib2 4513
END DESCRIPTION:
XS GIS Cut Line= 3
      1357092.85      6781537.91      1357299.01      6781088.33
      1356960.50      6780387.72
#Sta/Elev= 30
  4505.4 2526.42  4522.2 2526.29  4527.7 2525.42  4573.7 2523.63  4780.3 2518.28
  4837.6 2516.16  4860.6 2514.87  4878.1 2512.69  4906.6 2511.34  4935.1 2508.62
  4975.6 2506.25  4981.1 2506.68  5003.0 2506.30  5033.7 2507.56  5055.9 2507.30
  5079.3 2506.10  5079.8 2505.60  5093.6 2505.60  5094.1 2506.10  5137.4 2507.58
  5182.6 2510.38  5222.3 2515.24  5250.4 2517.59  5266.9 2517.81  5295.6 2519.28
  5346.4 2519.57  5355.8 2520.08  5466.8 2520.48  5623.1 2524.46  5778.1 2527.47
#Mann=3,-1,0
  4505.4    0.07       0  5079.3    0.07       0  5094.1    0.07       0
Bank Sta=5079.3,5094.1
Exp/Cntr=0.3,0.1

Chan Stop Cuts=-1