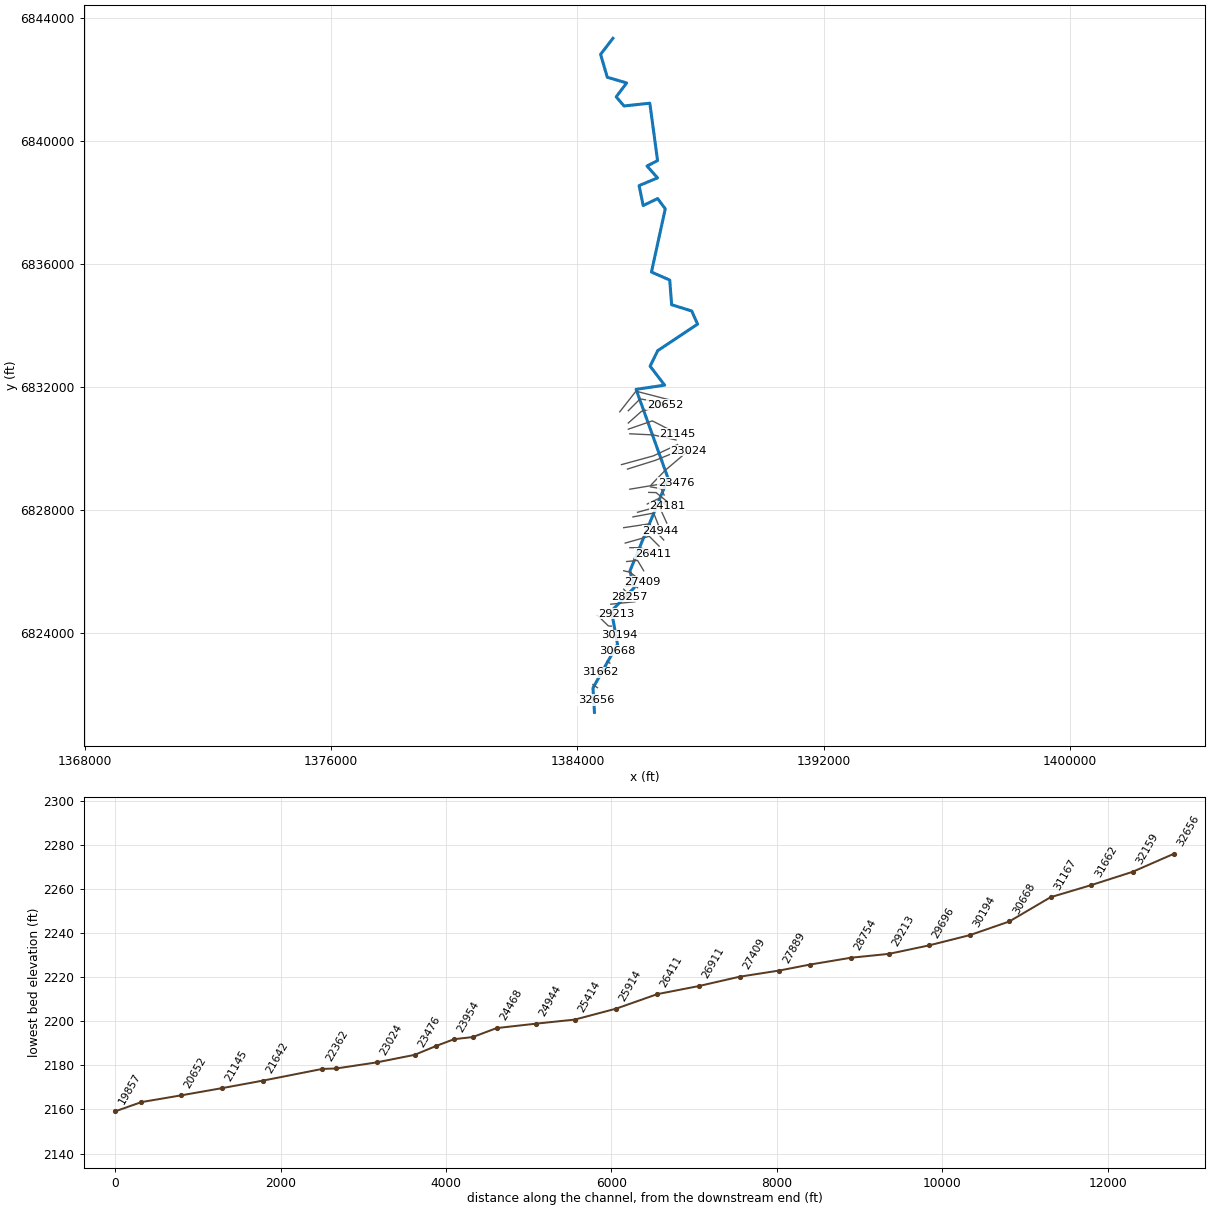
--- Sweetwater Creek Trib 20.prj (project) ---

Proj Title=Sweetwater Creek Trib 20 Base Level Engineering
Current Plan=p01
Default Exp/Contr=0.3,0.1
English Units
Geom File=g01
Flow File=f01
Plan File=p01
BEGIN DESCRIPTION:
Sweetwater Creek Trib 20
END DESCRIPTION:

--- Sweetwater Creek Trib 20.p01 (plan) ---

Plan Title=Multiple Run
Short Identifier=Multiple
Geom File=g01
Flow File=f01
Subcritical Flow
K Sum by GR= 0
Std Step Tol= 0.01
Critical Tol= 0.01
Num of Std Step Trials= 20
Max Error Tol= 0.3
Flow Tol Ratio= 0.001
Split Flow NTrial= 30
Split Flow Tol= 0.02
Split Flow Ratio= 0.02
Log Output Level= 0
Friction Slope Method= 1
Unsteady Friction Slope Method= 2
Unsteady Bridges Friction Slope Method= 1
Parabolic Critical Depth
Global Vel Dist=  1 , 1 , 1
Global Log Level= 0
CheckData=True
Encroach Param= -1, 0, 0, 0
BEGIN DESCRIPTION:
Multiple Run
END DESCRIPTION:

--- Sweetwater Creek Trib 20.f01 (steady flow) ---

Flow Title=Multiple
Number of Profiles=7
Profile Names=10-year,25-year,50-year,1pct_min,100-year,1pct_plu,500-year
River Rch & RM= Sweetwater Creek,Reach-1,32656
     358     520     661     418     833    1663    1342
River Rch & RM= Sweetwater Creek,Reach-1,30668
     400     585     745     472     941    1877    1522
River Rch & RM= Sweetwater Creek,Reach-1,23476
     665     996    1290     829    1655    3301    2760
River Rch & RM= Sweetwater Creek,Reach-1,19183
    1167    1789    2352    1532    3056    6098    5237
River Rch & RM= Sweetwater Creek,Reach-1,15261
    1365    2102    2772    1810    3612    7206    6221
River Rch & RM= Sweetwater Creek,Reach-1,11878
    1386    2132    2810    1834    3660    7302    6295
River Rch & RM= Sweetwater Creek,Reach-1,10254
    1543    2377    3135    2047    4085    8150    7031
River Rch & RM= Sweetwater Creek,Reach-1,4694
    1556    2393    3153    2055    4101    8183    7039
Boundary for River Rch & Prof#=Sweetwater Creek,Reach-1,1
Up Type=0
Dn Type=3
Dn Slope=0.005
Boundary for River Rch & Prof#=Sweetwater Creek,Reach-1,2
Up Type=0
Dn Type=3
Dn Slope=0.005
Boundary for River Rch & Prof#=Sweetwater Creek,Reach-1,3
Up Type=0
Dn Type=3
Dn Slope=0.005
Boundary for River Rch & Prof#=Sweetwater Creek,Reach-1,4
Up Type=0
Dn Type=3
Dn Slope=0.005
Boundary for River Rch & Prof#=Sweetwater Creek,Reach-1,5
Up Type=0
Dn Type=3
Dn Slope=0.005
Boundary for River Rch & Prof#=Sweetwater Creek,Reach-1,6
Up Type=0
Dn Type=3
Dn Slope=0.005
Boundary for River Rch & Prof#=Sweetwater Creek,Reach-1,7
Up Type=0
Dn Type=3
Dn Slope=0.005

--- Sweetwater Creek Trib 20.g01 (geometry) ---

Geom Title=Existing Conditions

River Reach=Sweetwater Creek,Reach-1
Reach XY= 30
      1384555.00      6821438.00      1384507.24      6822232.07
      1385304.00      6823648.29      1385107.23      6824732.10
      1385851.47      6825489.45      1385706.76      6826031.88
      1386947.49      6829037.99      1385906.83      6831932.27
      1386835.56      6832067.45      1386363.04      6832684.74
      1386610.45      6833190.47      1387905.39      6834050.96
      1387714.82      6834477.57      1387062.82      6834681.79
      1387000.08      6835482.96      1386407.01      6835743.68
      1386855.54      6837797.63      1386608.41      6838130.23
      1386137.86      6837904.02      1386005.51      6838551.88
      1386604.48      6838801.86      1386262.28      6839187.90
      1386605.42      6839362.58      1386353.87      6841228.59
      1385515.28      6841138.99      1385260.81      6841435.71
      1385601.65      6841886.75      1384971.64      6842071.32
      1384754.54      6842814.96      1385155.00      6843338.00

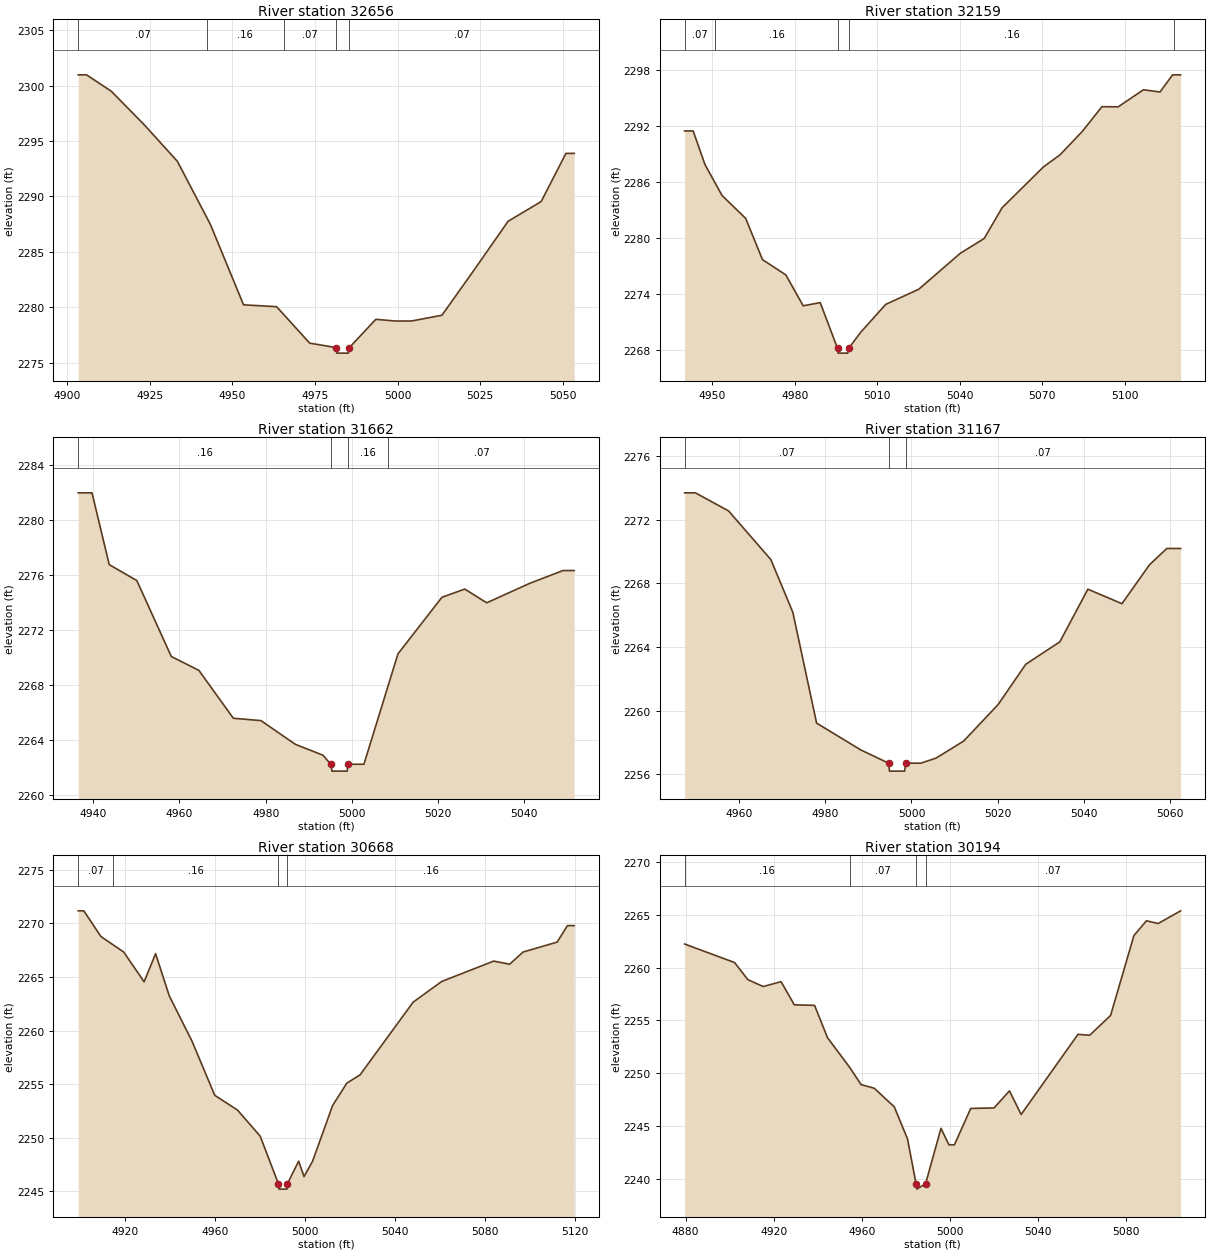
Type RM Length L Ch R = 1,32656,497,497,497
BEGIN DESCRIPTION:
Sweetwater Creek Trib 20 51.0
END DESCRIPTION:
XS GIS Cut Line= 3
      1384455.04      6821838.00      1384551.62      6821839.73
      1384605.00      6821838.00
#Sta/Elev= 24
  4903.4 2300.98  4905.9 2300.98  4913.4 2299.50  4923.4 2296.46  4933.4 2293.17
  4942.3 2288.09  4943.4 2287.46  4953.4 2280.22  4963.4 2280.05  4965.6 2279.33
  4973.4 2276.76  4981.4 2276.36  4981.6 2275.86  4985.1 2275.86  4985.4 2276.36
  4993.4 2278.91  4999.2 2278.76  5004.2 2278.76  5013.4 2279.28  5023.4 2283.48
  5033.4 2287.76  5043.4 2289.54  5050.9 2293.89  5053.4 2293.89
#Mann=5,-1,0
  4903.4    0.07       0  4942.3    0.16       0  4965.6    0.07       0
  4981.4    0.07       0  4985.4    0.07       0
Bank Sta=4981.4,4985.4
Exp/Cntr=0.3,0.1

Type RM Length L Ch R = 1,32159,497,497,497
BEGIN DESCRIPTION:
Sweetwater Creek Trib 20 50.0
END DESCRIPTION:
XS GIS Cut Line= 3
      1384504.97      6822338.02      1384553.99      6822303.42
      1384654.96      6822238.02
#Sta/Elev= 30
  4940.0 2291.51  4943.1 2291.51  4947.4 2287.91  4951.2 2285.88  4953.6 2284.60
  4962.2 2282.14  4968.3 2277.73  4976.8 2276.09  4983.1 2272.78  4989.3 2273.12
  4995.6 2268.21  4995.8 2267.71  4999.3 2267.71  4999.6 2268.21  5004.0 2269.94
  5013.1 2272.93  5025.1 2274.55  5040.2 2278.40  5048.9 2279.99  5055.4 2283.28
  5070.5 2287.67  5076.5 2288.96  5084.6 2291.47  5091.7 2294.11  5097.6 2294.09
  5106.8 2295.92  5112.8 2295.68  5117.4 2297.52  5118.0 2297.52  5120.3 2297.52
#Mann=5,-1,0
  4940.0    0.07       0  4951.2    0.16       0  4995.6    0.07       0
  4999.6    0.16       0  5118.0    0.07       0
Bank Sta=4995.6,4999.6
Exp/Cntr=0.3,0.1

Type RM Length L Ch R = 1,31662,495,495,495
BEGIN DESCRIPTION:
Sweetwater Creek Trib 20 49.0
END DESCRIPTION:
XS GIS Cut Line= 3
      1384654.97      6822788.02      1384704.48      6822748.26
      1384755.05      6822737.99
#Sta/Elev= 24
  4936.5 2282.00  4939.7 2282.00  4943.7 2276.77  4950.1 2275.61  4958.1 2270.08
  4964.5 2269.07  4972.5 2265.58  4978.9 2265.41  4986.9 2263.68  4993.3 2262.89
  4995.1 2262.23  4995.4 2261.73  4998.9 2261.73  4999.1 2262.23  5000.0 2262.23
  5002.8 2262.23  5008.5 2268.03  5010.7 2270.27  5020.9 2274.39  5026.2 2274.99
  5031.3 2273.99  5041.3 2275.41  5049.0 2276.34  5051.6 2276.34
#Mann=4,-1,0
  4936.5    0.16       0  4995.1    0.07       0  4999.1    0.16       0
  5008.5    0.07       0
Bank Sta=4995.1,4999.1
Exp/Cntr=0.3,0.1

Type RM Length L Ch R = 1,31167,499,499,499
BEGIN DESCRIPTION:
Sweetwater Creek Trib 20 48.0
END DESCRIPTION:
XS GIS Cut Line= 3
      1384955.03      6823087.99      1385006.55      6823077.36
      1385054.98      6823038.01
#Sta/Elev= 23
  4947.4 2273.70  4949.9 2273.70  4957.6 2272.56  4967.4 2269.50  4972.5 2266.18
  4978.0 2259.22  4988.2 2257.54  4994.7 2256.70  4994.9 2256.20  4998.4 2256.20
  4998.7 2256.70  5000.0 2256.70  5002.2 2256.70  5005.7 2257.02  5012.1 2258.09
  5020.1 2260.39  5026.5 2262.92  5034.4 2264.33  5040.9 2267.64  5048.8 2266.73
  5055.2 2269.18  5059.2 2270.20  5062.4 2270.20
#Mann=3,-1,0
  4947.4    0.07       0  4994.7    0.07       0  4998.7    0.07       0
Bank Sta=4994.7,4998.7
Exp/Cntr=0.3,0.1

Type RM Length L Ch R = 1,30668,474,474,474
BEGIN DESCRIPTION:
Sweetwater Creek Trib 20 47.0
END DESCRIPTION:
XS GIS Cut Line= 3
      1385104.99      6823488.00      1385204.84      6823503.17
      1385305.00      6823438.00
#Sta/Elev= 30
  4899.0 2271.17  4901.5 2271.17  4909.1 2268.77  4914.3 2268.03  4919.2 2267.33
  4928.3 2264.55  4933.4 2267.17  4939.5 2263.23  4949.6 2259.01  4959.7 2253.96
  4969.8 2252.59  4979.9 2250.15  4988.0 2245.71  4988.3 2245.21  4991.8 2245.21
  4992.0 2245.71  4997.0 2247.82  4999.4 2246.38  5003.2 2247.82  5012.1 2253.01
  5018.4 2255.09  5024.3 2255.87  5047.9 2262.65  5060.6 2264.58  5083.7 2266.48
  5090.8 2266.19  5096.8 2267.33  5111.9 2268.25  5116.5 2269.79  5119.5 2269.79
#Mann=4,-1,0
  4899.0    0.07       0  4914.3    0.16       0  4988.0    0.07       0
  4992.0    0.16       0
Bank Sta=4988,4992
Exp/Cntr=0.3,0.1

Type RM Length L Ch R = 1,30194,498,498,498
BEGIN DESCRIPTION:
Sweetwater Creek Trib 20 46.0
END DESCRIPTION:
XS GIS Cut Line= 3
      1385155.00      6823838.00      1385256.04      6823903.48
      1385354.99      6823938.00
#Sta/Elev= 30
  4879.6 2262.23  4902.3 2260.48  4908.3 2258.86  4915.3 2258.21  4923.4 2258.67
  4929.4 2256.48  4938.6 2256.43  4944.5 2253.36  4954.5 2250.58  4959.7 2248.94
  4965.7 2248.59  4974.8 2246.83  4980.8 2243.80  4984.7 2239.55  4985.0 2239.05
  4989.0 2239.55  4996.0 2244.80  4999.6 2243.24  5002.1 2243.24  5009.5 2246.68
  5020.1 2246.73  5027.1 2248.34  5032.4 2246.11  5058.2 2253.69  5063.5 2253.60
  5073.0 2255.47  5083.6 2263.03  5089.3 2264.43  5094.6 2264.17  5104.8 2265.37
#Mann=4,-1,0
  4879.6    0.16       0  4954.5    0.07       0  4984.7    0.07       0
  4989.0    0.07       0
Bank Sta=4984.7,4989
Exp/Cntr=0.3,0.1

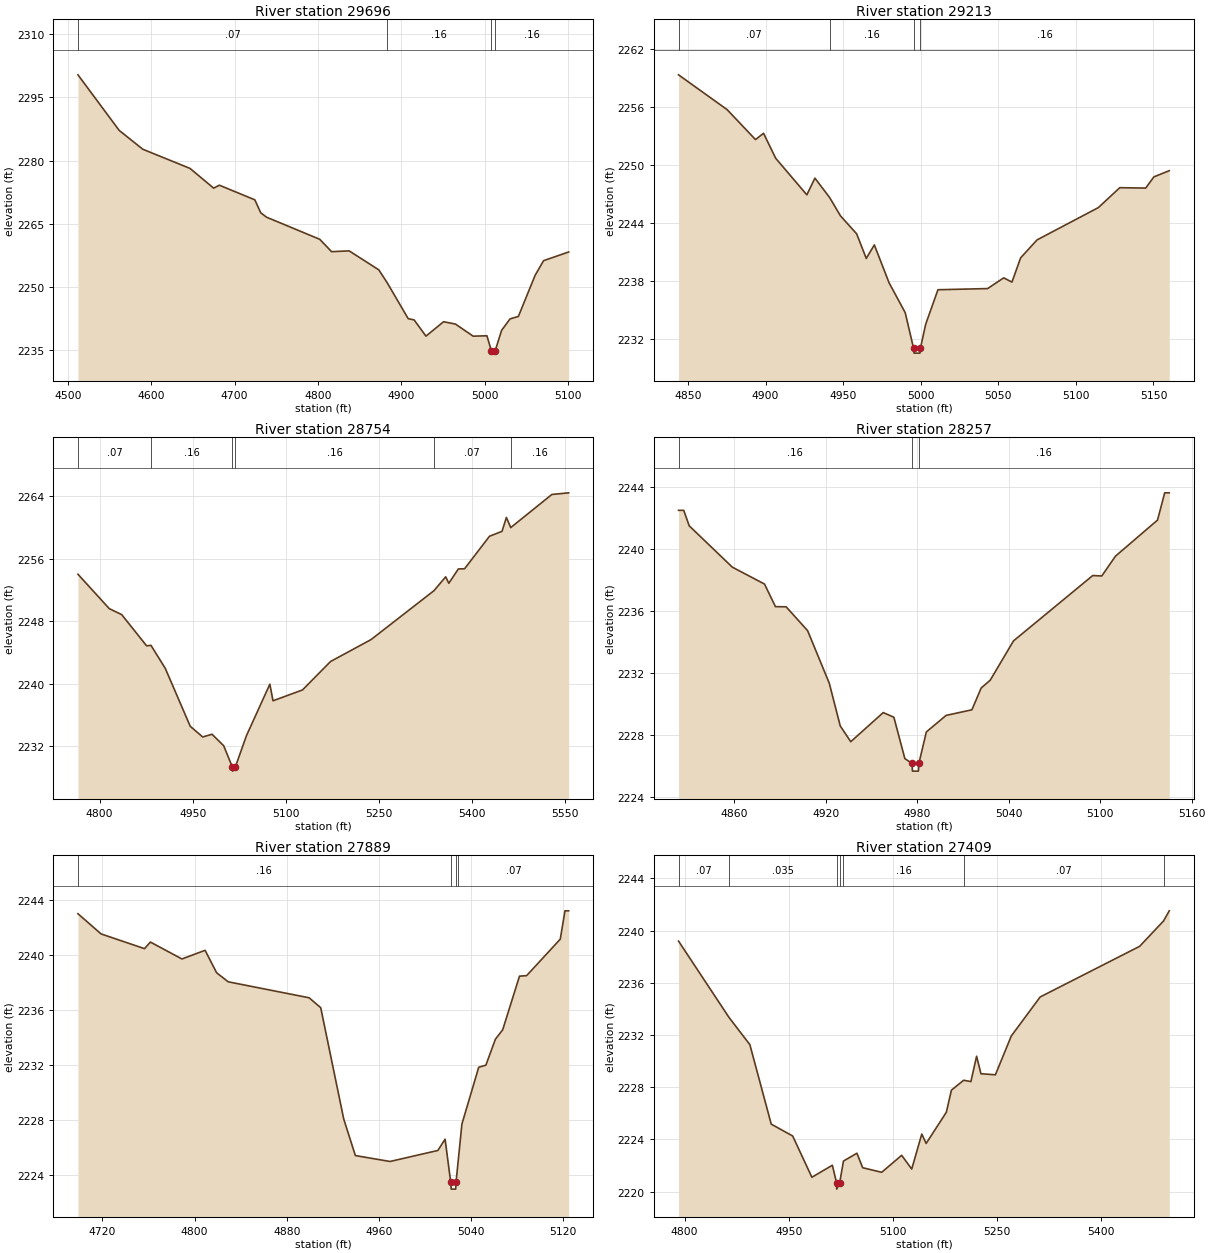
Type RM Length L Ch R = 1,29696,483,483,483
BEGIN DESCRIPTION:
Sweetwater Creek Trib 20 45.0
END DESCRIPTION:
XS GIS Cut Line= 3
      1384655.02      6824587.98      1385004.88      6824248.05
      1385104.97      6824238.00
#Sta/Elev= 30
  4512.2 2300.31  4561.7 2287.13  4590.0 2282.67  4646.6 2278.13  4674.9 2273.46
  4681.8 2274.15  4724.3 2270.69  4731.4 2267.61  4738.4 2266.57  4802.2 2261.33
  4816.3 2258.40  4837.4 2258.59  4872.9 2254.10  4882.8 2251.11  4908.2 2242.53
  4915.3 2242.23  4929.5 2238.39  4950.6 2241.80  4964.8 2241.25  4986.1 2238.38
  5002.6 2238.47  5008.0 2234.86  5008.3 2234.36  5012.4 2234.86  5020.2 2239.76
  5030.3 2242.47  5040.3 2243.05  5060.4 2252.81  5070.5 2256.27  5100.6 2258.33
#Mann=4,-1,0
  4512.2    0.07       0  4882.8    0.16       0  5008.0    0.07       0
  5012.4    0.16       0
Bank Sta=5008,5012.4
Exp/Cntr=0.3,0.1

Type RM Length L Ch R = 1,29213,459,459,459
BEGIN DESCRIPTION:
Sweetwater Creek Trib 20 44.0
END DESCRIPTION:
XS GIS Cut Line= 3
      1384955.02      6824737.99      1385104.56      6824693.19
      1385254.96      6824638.02
#Sta/Elev= 30
  4843.9 2259.33  4875.2 2255.73  4893.5 2252.63  4898.7 2253.28  4906.5 2250.70
  4926.6 2246.91  4931.8 2248.64  4941.3 2246.63  4948.3 2244.73  4958.7 2242.88
  4964.9 2240.33  4970.1 2241.73  4979.6 2237.81  4990.0 2234.72  4995.4 2231.03
  4995.7 2230.53  4999.5 2230.53  4999.8 2231.03  5003.2 2233.52  5011.1 2237.09
  5043.1 2237.21  5053.5 2238.32  5058.8 2237.88  5064.4 2240.39  5075.0 2242.25
  5114.5 2245.59  5128.3 2247.65  5145.0 2247.61  5150.3 2248.77  5160.2 2249.41
#Mann=4,-1,0
  4843.9    0.07       0  4941.3    0.16       0  4995.4    0.07       0
  4999.8    0.16       0
Bank Sta=4995.4,4999.8
Exp/Cntr=0.3,0.1

Type RM Length L Ch R = 1,28754,497,497,497
BEGIN DESCRIPTION:
Sweetwater Creek Trib 20 43.0
END DESCRIPTION:
XS GIS Cut Line= 3
      1385084.79      6824951.50      1385318.63      6824974.88
      1385871.95      6825033.33
#Sta/Elev= 30
  4765.0 2254.03  4815.5 2249.62  4835.6 2248.85  4875.7 2244.85  4882.8 2244.91
  4905.9 2241.95  4946.1 2234.53  4966.2 2233.16  4981.2 2233.51  5000.0 2232.04
  5014.2 2229.28  5014.5 2228.78  5018.7 2229.28  5036.6 2233.30  5074.5 2239.93
  5079.6 2237.80  5127.1 2239.19  5172.4 2242.84  5237.7 2245.65  5339.0 2251.91
  5358.1 2253.70  5363.1 2252.87  5378.5 2254.71  5388.5 2254.73  5428.7 2258.90
  5448.9 2259.53  5456.0 2261.31  5463.0 2260.01  5529.3 2264.26  5556.4 2264.47
#Mann=6,-1,0
  4765.0    0.07       0  4882.8    0.16       0  5014.2    0.07       0
  5018.7    0.16       0  5339.0    0.07       0  5463.0    0.16       0
Bank Sta=5014.2,5018.7
Exp/Cntr=0.3,0.1

Type RM Length L Ch R = 1,28257,368,368,368
BEGIN DESCRIPTION:
Sweetwater Creek Trib 20 42.0
END DESCRIPTION:
XS GIS Cut Line= 3
      1385505.03      6825437.97      1385628.31      6825311.38
      1385705.01      6825187.98
#Sta/Elev= 30
  4823.3 2242.51  4826.7 2242.51  4830.3 2241.51  4858.6 2238.84  4879.7 2237.75
  4886.9 2236.29  4893.9 2236.28  4908.0 2234.74  4922.2 2231.35  4929.4 2228.59
  4936.3 2227.57  4957.6 2229.45  4964.6 2229.15  4971.8 2226.48  4976.5 2226.17
  4976.8 2225.67  4980.7 2225.67  4981.0 2226.17  4985.9 2228.20  4998.9 2229.27
  5015.8 2229.63  5021.9 2231.04  5027.8 2231.54  5043.1 2234.08  5095.1 2238.30
  5101.0 2238.27  5110.0 2239.55  5137.6 2241.88  5142.3 2243.64  5145.3 2243.64
#Mann=3,-1,0
  4823.3    0.16       0  4976.5    0.07       0  4981.0    0.16       0
Bank Sta=4976.5,4981
Exp/Cntr=0.3,0.1

Type RM Length L Ch R = 1,27889,480,480,480
BEGIN DESCRIPTION:
Sweetwater Creek Trib 20 41.0
END DESCRIPTION:
XS GIS Cut Line= 3
      1385554.97      6825538.00      1385855.24      6825562.92
      1385955.03      6825487.98
#Sta/Elev= 30
  4698.7 2243.01  4718.8 2241.54  4756.5 2240.47  4761.6 2240.95  4789.0 2239.72
  4809.1 2240.35  4819.1 2238.72  4829.2 2238.06  4899.4 2236.90  4909.5 2236.18
  4929.5 2228.08  4939.6 2225.43  4969.7 2225.00  5011.2 2225.80  5017.5 2226.62
  5022.4 2223.49  5022.8 2222.99  5026.7 2222.99  5027.0 2223.49  5028.8 2224.98
  5032.1 2227.72  5046.7 2231.85  5052.9 2232.00  5061.2 2233.89  5067.5 2234.57
  5082.1 2238.47  5088.3 2238.51  5117.5 2241.16  5121.6 2243.22  5124.8 2243.22
#Mann=4,-1,0
  4698.7    0.16       0  5022.4    0.07       0  5027.0    0.16       0
  5028.8    0.07       0
Bank Sta=5022.4,5027
Exp/Cntr=0.3,0.1

Type RM Length L Ch R = 1,27409,498,498,498
BEGIN DESCRIPTION:
Sweetwater Creek Trib 20 40.0
END DESCRIPTION:
XS GIS Cut Line= 3
      1385505.01      6826038.00      1385708.14      6825989.64
      1386105.01      6825687.99
#Sta/Elev= 30
  4791.2 2239.19  4864.0 2233.34  4894.0 2231.26  4924.8 2225.17  4955.7 2224.26
  4983.4 2221.10  5012.9 2222.02  5018.9 2220.69  5019.2 2220.19  5023.5 2220.69
  5028.9 2222.34  5048.3 2222.94  5056.6 2221.83  5084.0 2221.48  5112.8 2222.78
  5127.3 2221.73  5141.8 2224.41  5148.1 2223.69  5177.2 2226.08  5184.5 2227.77
  5202.1 2228.53  5212.6 2228.43  5220.8 2230.37  5227.1 2229.03  5247.9 2228.95
  5270.8 2231.92  5312.4 2234.91  5455.8 2238.79  5490.2 2240.73  5498.5 2241.51
#Mann=7,-1,0
  4791.2    0.07       0  4864.0   0.035       0  5018.9   0.035       0
  5023.5   0.035       0  5028.9    0.16       0  5202.1    0.07       0
  5490.2   0.035       0
Bank Sta=5018.9,5023.5
Exp/Cntr=0.3,0.1

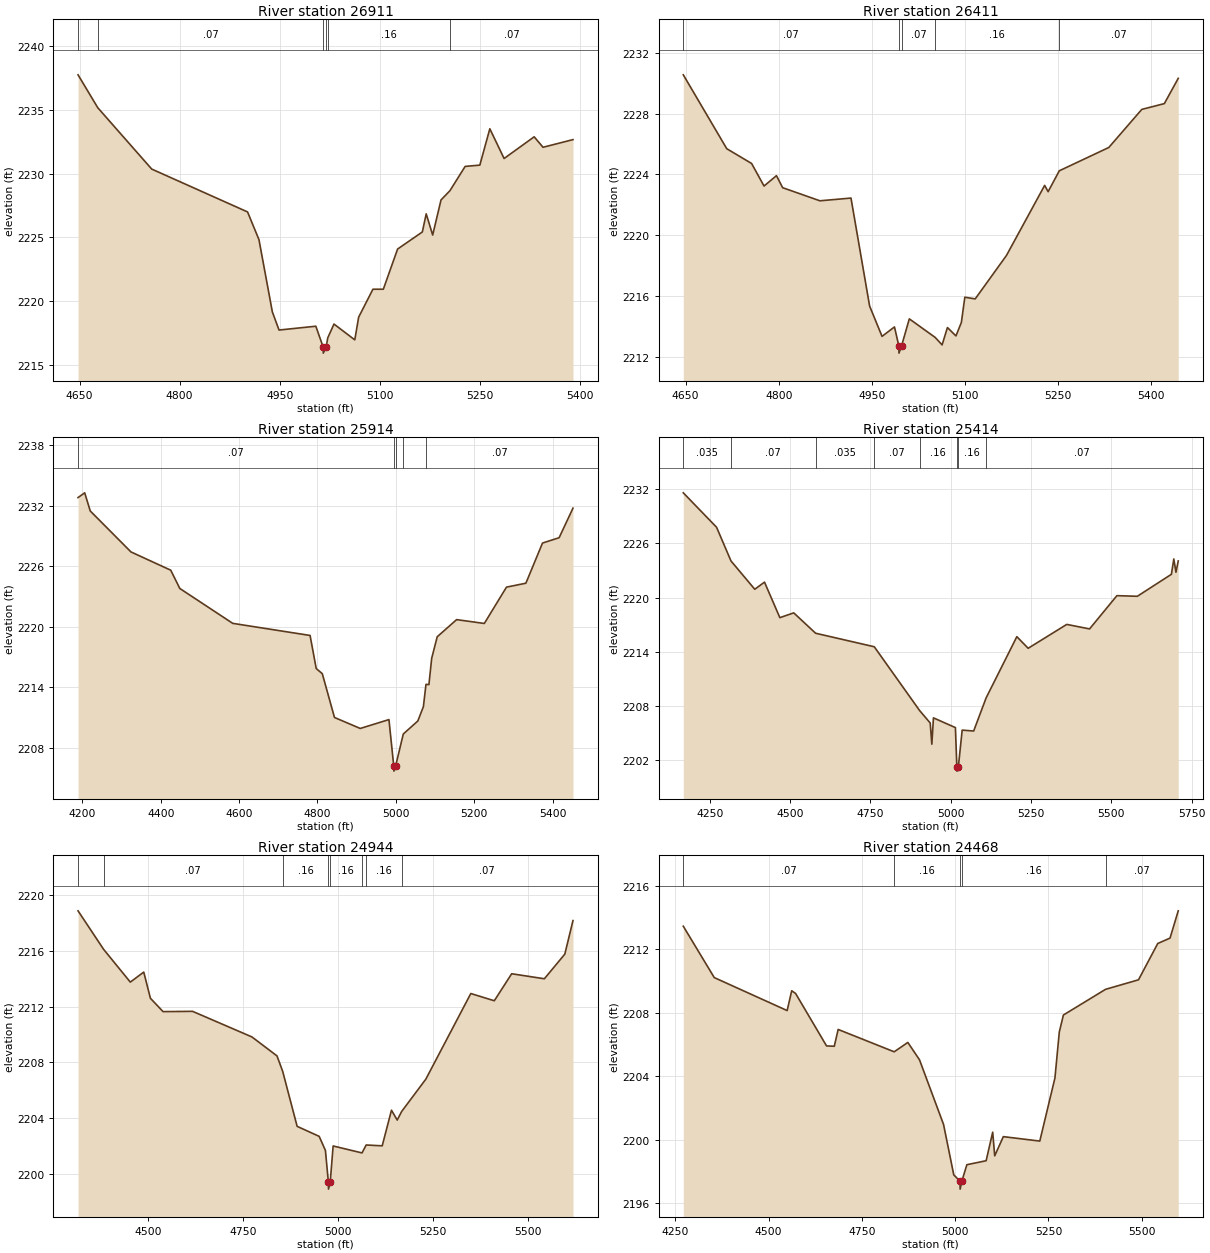
Type RM Length L Ch R = 1,26911,500,500,500
BEGIN DESCRIPTION:
Sweetwater Creek Trib 20 39.0
END DESCRIPTION:
XS GIS Cut Line= 3
      1385605.04      6826338.00      1385955.70      6826372.94
      1386155.02      6826037.96
#Sta/Elev= 30
  4647.6 2237.74  4677.2 2235.16  4758.1 2230.35  4901.8 2226.99  4918.9 2224.82
  4939.0 2219.15  4949.0 2217.73  5004.2 2218.03  5015.0 2216.42  5015.4 2215.92
  5019.7 2216.42  5022.1 2217.12  5031.4 2218.20  5062.6 2216.96  5068.4 2218.74
  5089.8 2220.93  5105.4 2220.93  5126.8 2224.08  5163.9 2225.42  5169.7 2226.84
  5179.4 2225.18  5191.9 2227.93  5205.2 2228.65  5228.1 2230.56  5250.1 2230.66
  5265.1 2233.51  5286.5 2231.18  5331.6 2232.88  5344.9 2232.06  5389.8 2232.66
#Mann=6,-1,0
  4647.6   0.035       0  4677.2    0.07       0  5015.0    0.07       0
  5019.7    0.07       0  5022.1    0.16       0  5205.2    0.07       0
Bank Sta=5015,5019.7
Exp/Cntr=0.3,0.1

Type RM Length L Ch R = 1,26411,497,497,497
BEGIN DESCRIPTION:
Sweetwater Creek Trib 20 38.0
END DESCRIPTION:
XS GIS Cut Line= 3
      1385705.01      6826788.00      1386058.61      6826786.50
      1386454.99      6826588.01
#Sta/Elev= 30
  4646.4 2230.54  4716.4 2225.69  4756.4 2224.72  4776.4 2223.24  4796.4 2223.92
  4806.4 2223.13  4866.4 2222.27  4916.4 2222.45  4946.4 2215.36  4966.4 2213.37
  4986.4 2213.99  4993.3 2212.77  4993.7 2212.27  4998.0 2212.77  5010.3 2214.52
  5052.0 2213.30  5063.1 2212.81  5071.7 2213.95  5085.4 2213.40  5094.1 2214.28
  5099.7 2215.94  5116.4 2215.83  5166.7 2218.68  5228.2 2223.28  5233.8 2222.87
  5251.8 2224.24  5331.5 2225.77  5384.6 2228.27  5420.9 2228.65  5443.3 2230.31
#Mann=5,-1,0
  4646.4    0.07       0  4993.3    0.07       0  4998.0    0.07       0
  5052.0    0.16       0  5251.8    0.07       0
Bank Sta=4993.3,4998
Exp/Cntr=0.3,0.1

Type RM Length L Ch R = 1,25914,500,500,500
BEGIN DESCRIPTION:
Sweetwater Creek Trib 20 37.0
END DESCRIPTION:
XS GIS Cut Line= 3
      1385555.01      6826938.00      1386335.58      6827158.09
      1386655.00      6826838.00
#Sta/Elev= 30
  4189.0 2232.82  4206.0 2233.29  4220.2 2231.49  4324.1 2227.43  4425.6 2225.62
  4448.7 2223.81  4583.8 2220.35  4781.2 2219.15  4796.9 2215.87  4812.4 2215.36
  4843.5 2211.02  4909.3 2209.93  4982.5 2210.81  4994.8 2206.20  4995.1 2205.70
  4999.5 2206.20  5019.1 2209.38  5056.2 2210.67  5070.4 2212.09  5077.0 2214.30
  5084.5 2214.28  5091.6 2216.89  5105.7 2219.02  5155.2 2220.72  5225.9 2220.34
  5282.5 2223.94  5332.0 2224.33  5374.4 2228.31  5416.8 2228.84  5452.2 2231.77
#Mann=5,-1,0
  4189.0    0.07       0  4994.8    0.07       0  4999.5    0.07       0
  5019.1    0.16       0  5077.0    0.07       0
Bank Sta=4994.8,4999.5
Exp/Cntr=0.3,0.1

Type RM Length L Ch R = 1,25414,470,470,470
BEGIN DESCRIPTION:
Sweetwater Creek Trib 20 36.0
END DESCRIPTION:
XS GIS Cut Line= 3
      1385504.97      6827438.00      1386328.12      6827561.73
      1386804.99      6827038.01
#Sta/Elev= 30
  4167.6 2231.62  4271.2 2227.80  4316.1 2224.06  4390.1 2220.92  4420.4 2221.71
  4468.2 2217.77  4511.4 2218.30  4579.5 2216.04  4762.1 2214.54  4903.3 2207.46
  4936.2 2206.08  4941.3 2203.73  4946.3 2206.65  5014.7 2205.57  5019.1 2201.24
  5019.4 2200.74  5023.9 2201.24  5035.7 2205.29  5071.5 2205.19  5110.3 2208.87
  5205.9 2215.66  5241.1 2214.37  5361.3 2217.02  5432.3 2216.52  5517.4 2220.21
  5580.9 2220.14  5687.0 2222.58  5694.5 2224.28  5701.2 2222.81  5708.3 2224.06
#Mann=8,-1,0
  4167.6   0.035       0  4316.1    0.07       0  4579.5   0.035       0
  4762.1    0.07       0  4903.3    0.16       0  5019.1    0.07       0
  5023.9    0.16       0  5110.3    0.07       0
Bank Sta=5019.1,5023.9
Exp/Cntr=0.3,0.1

Type RM Length L Ch R = 1,24944,476,476,476
BEGIN DESCRIPTION:
Sweetwater Creek Trib 20 35.0
END DESCRIPTION:
XS GIS Cut Line= 3
      1385805.02      6827788.00      1386478.24      6827912.31
      1386705.02      6827337.96
#Sta/Elev= 30
  4315.4 2218.88  4382.8 2216.11  4452.9 2213.76  4488.3 2214.48  4505.8 2212.60
  4539.1 2211.64  4616.8 2211.66  4773.0 2209.82  4838.8 2208.46  4853.7 2207.36
  4891.8 2203.40  4949.8 2202.68  4966.2 2201.67  4974.0 2199.39  4974.3 2198.89
  4978.8 2199.39  4986.5 2201.99  5062.5 2201.49  5073.4 2202.06  5115.6 2202.00
  5140.0 2204.56  5155.1 2203.85  5166.6 2204.46  5230.4 2206.79  5348.7 2212.94
  5410.5 2212.42  5456.2 2214.36  5542.2 2214.00  5596.0 2215.77  5617.5 2218.18
#Mann=8,-1,0
  4315.4   0.035       0  4382.8    0.07       0  4853.7    0.16       0
  4974.0    0.07       0  4978.8    0.16       0  5062.5    0.07       0
  5073.4    0.16       0  5166.6    0.07       0
Bank Sta=4974,4978.8
Exp/Cntr=0.3,0.1

Type RM Length L Ch R = 1,24468,287,287,287
BEGIN DESCRIPTION:
Sweetwater Creek Trib 20 34.0
END DESCRIPTION:
XS GIS Cut Line= 3
      1385955.01      6827938.00      1386657.19      6828132.03
      1386904.99      6827588.01
#Sta/Elev= 30
  4271.5 2213.46  4354.5 2210.22  4549.8 2208.14  4562.0 2209.39  4572.4 2209.22
  4655.4 2205.91  4676.1 2205.89  4686.5 2206.95  4836.6 2205.54  4873.2 2206.13
  4904.4 2205.04  4968.9 2200.96  4996.3 2197.78  5013.0 2197.38  5013.4 2196.88
  5017.9 2197.38  5031.4 2198.42  5083.0 2198.67  5100.6 2200.47  5106.0 2198.98
  5129.1 2200.19  5226.8 2199.91  5267.4 2203.89  5279.1 2206.79  5290.1 2207.86
  5403.1 2209.48  5491.3 2210.08  5542.9 2212.37  5575.8 2212.71  5597.8 2214.43
#Mann=5,-1,0
  4271.5    0.07       0  4836.6    0.16       0  5013.0    0.07       0
  5017.9    0.16       0  5403.1    0.07       0
Bank Sta=5013,5017.9
Exp/Cntr=0.3,0.1

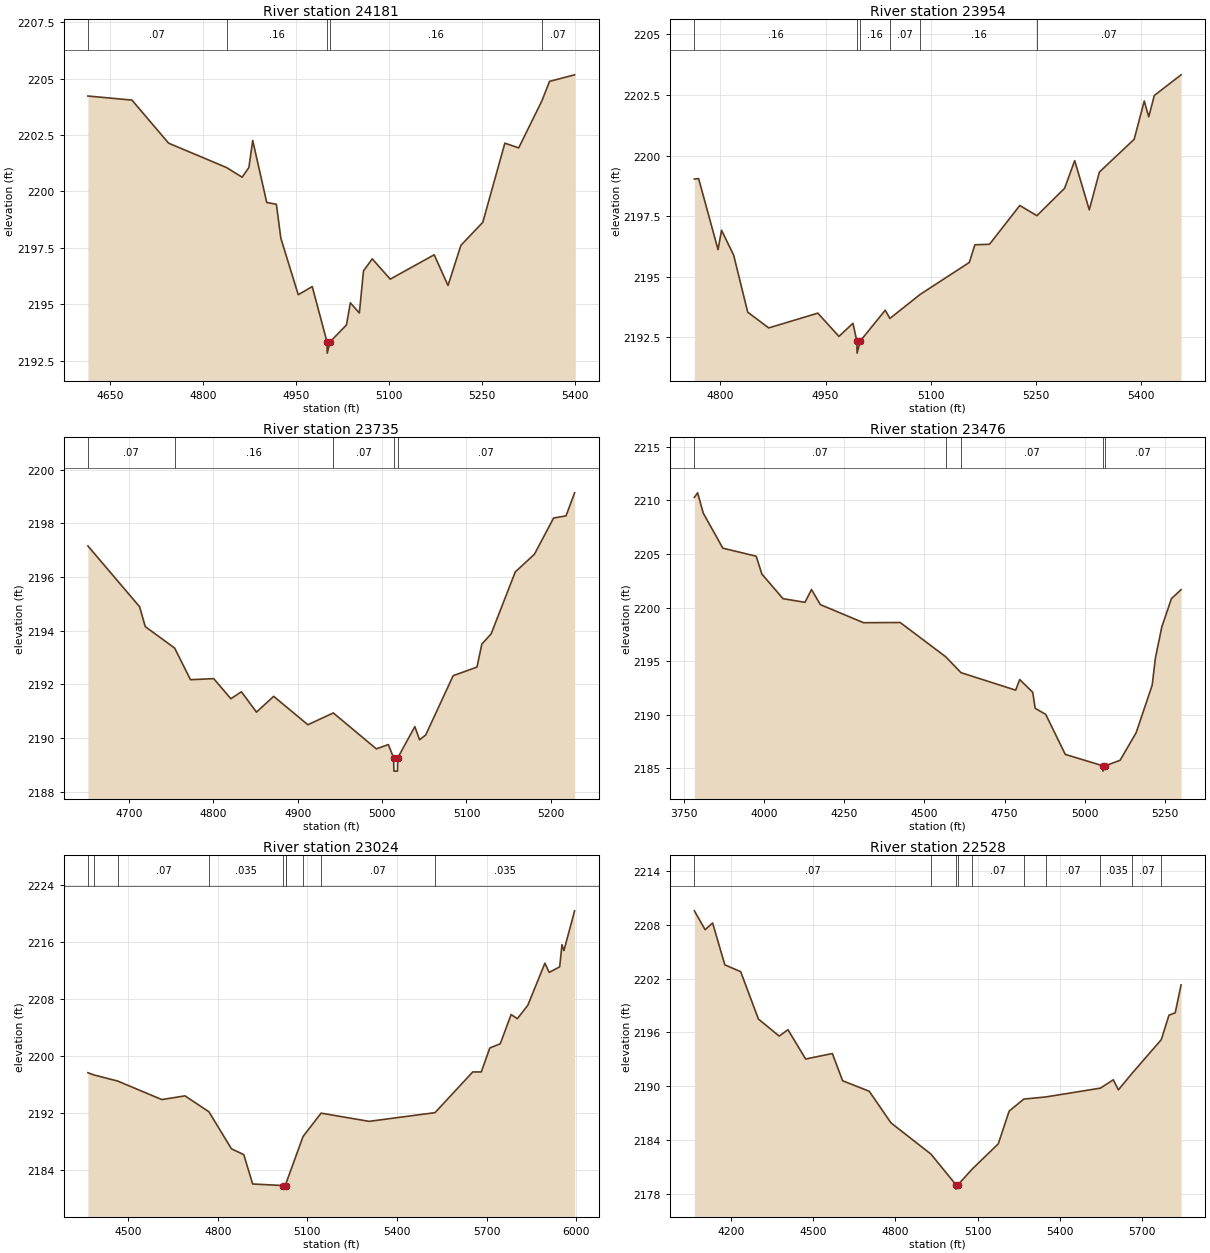
Type RM Length L Ch R = 1,24181,227,227,227
BEGIN DESCRIPTION:
Sweetwater Creek Trib 20 4151
END DESCRIPTION:
XS GIS Cut Line= 3
      1386270.98      6828207.34      1386618.57      6828374.76
      1386933.78      6828129.64
#Sta/Elev= 30
  4614.2 2204.23  4685.3 2204.05  4744.4 2202.14  4837.8 2201.06  4863.0 2200.63
  4873.9 2201.06  4880.1 2202.26  4902.7 2199.51  4918.3 2199.43  4925.4 2197.93
  4953.5 2195.42  4976.1 2195.78  4999.9 2193.33  5000.3 2192.83  5004.8 2193.33
  5031.3 2194.08  5037.6 2195.06  5052.1 2194.61  5058.8 2196.48  5072.9 2197.01
  5101.9 2196.11  5172.8 2197.19  5195.1 2195.83  5215.9 2197.61  5251.2 2198.63
  5286.8 2202.14  5309.1 2201.93  5346.4 2204.01  5358.9 2204.88  5399.3 2205.17
#Mann=5,-1,0
  4614.2    0.07       0  4837.8    0.16       0  4999.9    0.07       0
  5004.8    0.16       0  5346.4    0.07       0
Bank Sta=4999.9,5004.8
Exp/Cntr=0.3,0.1

Type RM Length L Ch R = 1,23954,219,219,219
BEGIN DESCRIPTION:
Sweetwater Creek Trib 20 4150
END DESCRIPTION:
XS GIS Cut Line= 3
      1386318.92      6828583.98      1386556.03      6828577.57
      1386911.56      6828290.59
#Sta/Elev= 30
  4762.8 2199.03  4768.9 2199.05  4796.6 2196.12  4801.6 2196.92  4818.9 2195.89
  4838.9 2193.54  4868.9 2192.89  4938.9 2193.50  4969.0 2192.54  4989.0 2193.08
  4994.5 2192.35  4994.9 2191.85  4999.4 2192.35  5035.0 2193.62  5041.7 2193.28
  5084.7 2194.27  5154.9 2195.59  5162.9 2196.32  5183.7 2196.34  5226.9 2197.94
  5251.3 2197.52  5290.8 2198.65  5305.2 2199.79  5326.0 2197.76  5340.4 2199.32
  5390.0 2200.67  5404.4 2202.25  5410.8 2201.60  5418.8 2202.48  5456.9 2203.33
#Mann=6,-1,0
  4762.8    0.16       0  4994.5    0.07       0  4999.4    0.16       0
  5041.7    0.07       0  5084.7    0.16       0  5251.3    0.07       0
Bank Sta=4994.5,4999.4
Exp/Cntr=0.3,0.1

Type RM Length L Ch R = 1,23735,259,259,259
BEGIN DESCRIPTION:
Sweetwater Creek Trib 20 33.0
END DESCRIPTION:
XS GIS Cut Line= 3
      1386377.99      6828763.01      1386721.67      6828704.65
      1386819.90      6828498.78
#Sta/Elev= 30
  4651.4 2197.16  4712.7 2194.89  4719.4 2194.15  4754.2 2193.35  4773.0 2192.17
  4800.5 2192.21  4820.8 2191.46  4833.3 2191.72  4851.2 2190.96  4871.5 2191.55
  4912.1 2190.49  4942.2 2190.93  4993.2 2189.59  5007.4 2189.75  5013.6 2189.26
  5014.0 2188.76  5018.2 2188.76  5018.6 2189.26  5038.8 2190.42  5044.4 2189.93
  5051.7 2190.11  5084.2 2192.32  5112.4 2192.64  5118.2 2193.50  5129.2 2193.88
  5157.8 2196.19  5180.5 2196.85  5203.2 2198.20  5217.9 2198.28  5228.1 2199.14
#Mann=5,-1,0
  4651.4    0.07       0  4754.2    0.16       0  4942.2    0.07       0
  5013.6    0.07       0  5018.6    0.07       0
Bank Sta=5013.6,5018.6
Exp/Cntr=0.3,0.1

Type RM Length L Ch R = 1,23476,452,452,452
BEGIN DESCRIPTION:
Sweetwater Creek Trib 20 32.0
END DESCRIPTION:
XS GIS Cut Line= 3
      1385704.95      6828687.99      1386905.00      6828888.00
      1387205.00      6828888.00
#Sta/Elev= 30
  3783.4 2210.27  3793.6 2210.70  3811.3 2208.80  3872.2 2205.54  3976.1 2204.79
  3993.8 2203.13  4059.7 2200.83  4128.1 2200.49  4148.4 2201.68  4176.3 2200.27
  4310.6 2198.59  4424.7 2198.61  4566.4 2195.42  4614.4 2193.93  4784.6 2192.30
  4797.2 2193.29  4837.8 2192.10  4845.4 2190.61  4878.3 2190.04  4939.2 2186.31
  5056.0 2185.25  5056.5 2184.75  5064.0 2185.25  5110.0 2185.76  5160.0 2188.33
  5210.0 2192.77  5220.0 2195.29  5240.0 2198.20  5270.0 2200.84  5300.0 2201.67
#Mann=5,-1,0
  3783.4    0.07       0  4566.4    0.16       0  4614.4    0.07       0
  5056.0    0.07       0  5064.0    0.07       0
Bank Sta=5056,5064
Exp/Cntr=0.3,0.1

Type RM Length L Ch R = 1,23024,496,496,496
BEGIN DESCRIPTION:
Sweetwater Creek Trib 20 31.0
END DESCRIPTION:
XS GIS Cut Line= 3
      1386404.98      6828837.98      1386846.60      6829293.98
      1387605.03      6829938.03
#Sta/Elev= 30
  4365.2 2197.68  4386.2 2197.36  4465.3 2196.51  4612.8 2193.92  4690.5 2194.44
  4770.5 2192.21  4846.1 2187.02  4887.3 2186.21  4916.9 2182.10  5019.4 2181.88
  5019.9 2181.38  5027.5 2181.88  5029.6 2182.30  5085.8 2188.76  5146.2 2192.02
  5306.8 2190.87  5527.6 2192.09  5653.9 2197.79  5682.5 2197.79  5711.0 2201.14
  5746.1 2201.74  5782.4 2205.83  5803.3 2205.25  5838.4 2207.13  5895.5 2213.02
  5909.8 2211.73  5945.0 2212.50  5952.7 2215.61  5959.2 2214.78  5995.0 2220.35
#Mann=10,-1,0
  4365.2    0.07       0  4386.2   0.035       0  4465.3    0.07       0
  4770.5   0.035       0  5019.4   0.035       0  5027.5   0.035       0
  5029.6    0.07       0  5085.8   0.035       0  5146.2    0.07       0
  5527.6   0.035       0
Bank Sta=5019.4,5027.5
Exp/Cntr=0.3,0.1

Type RM Length L Ch R = 1,22528,166,166,166
BEGIN DESCRIPTION:
Sweetwater Creek Trib 20 30.0
END DESCRIPTION:
XS GIS Cut Line= 3
      1385628.60      6829342.36      1386521.83      6829621.40
      1387304.96      6829937.98
#Sta/Elev= 30
  4064.2 2209.54  4103.7 2207.44  4131.0 2208.19  4175.7 2203.53  4233.7 2202.77
  4298.6 2197.50  4374.7 2195.60  4406.6 2196.31  4471.5 2193.05  4569.0 2193.66
  4606.7 2190.63  4704.1 2189.46  4783.3 2185.95  4929.7 2182.47  5020.8 2179.07
  5021.3 2178.57  5029.1 2179.07  5080.9 2180.81  5176.0 2183.61  5215.7 2187.25
  5269.3 2188.59  5350.0 2188.83  5549.8 2189.81  5596.7 2190.74  5615.4 2189.62
  5666.7 2191.50  5772.2 2195.20  5800.5 2197.93  5823.2 2198.19  5844.7 2201.30
#Mann=10,-1,0
  4064.2    0.07       0  4929.7   0.035       0  5020.8   0.035       0
  5029.1   0.035       0  5080.9    0.07       0  5269.3   0.035       0
  5350.0    0.07       0  5549.8   0.035       0  5666.7    0.07       0
  5772.2   0.035       0
Bank Sta=5020.8,5029.1
Exp/Cntr=0.3,0.1

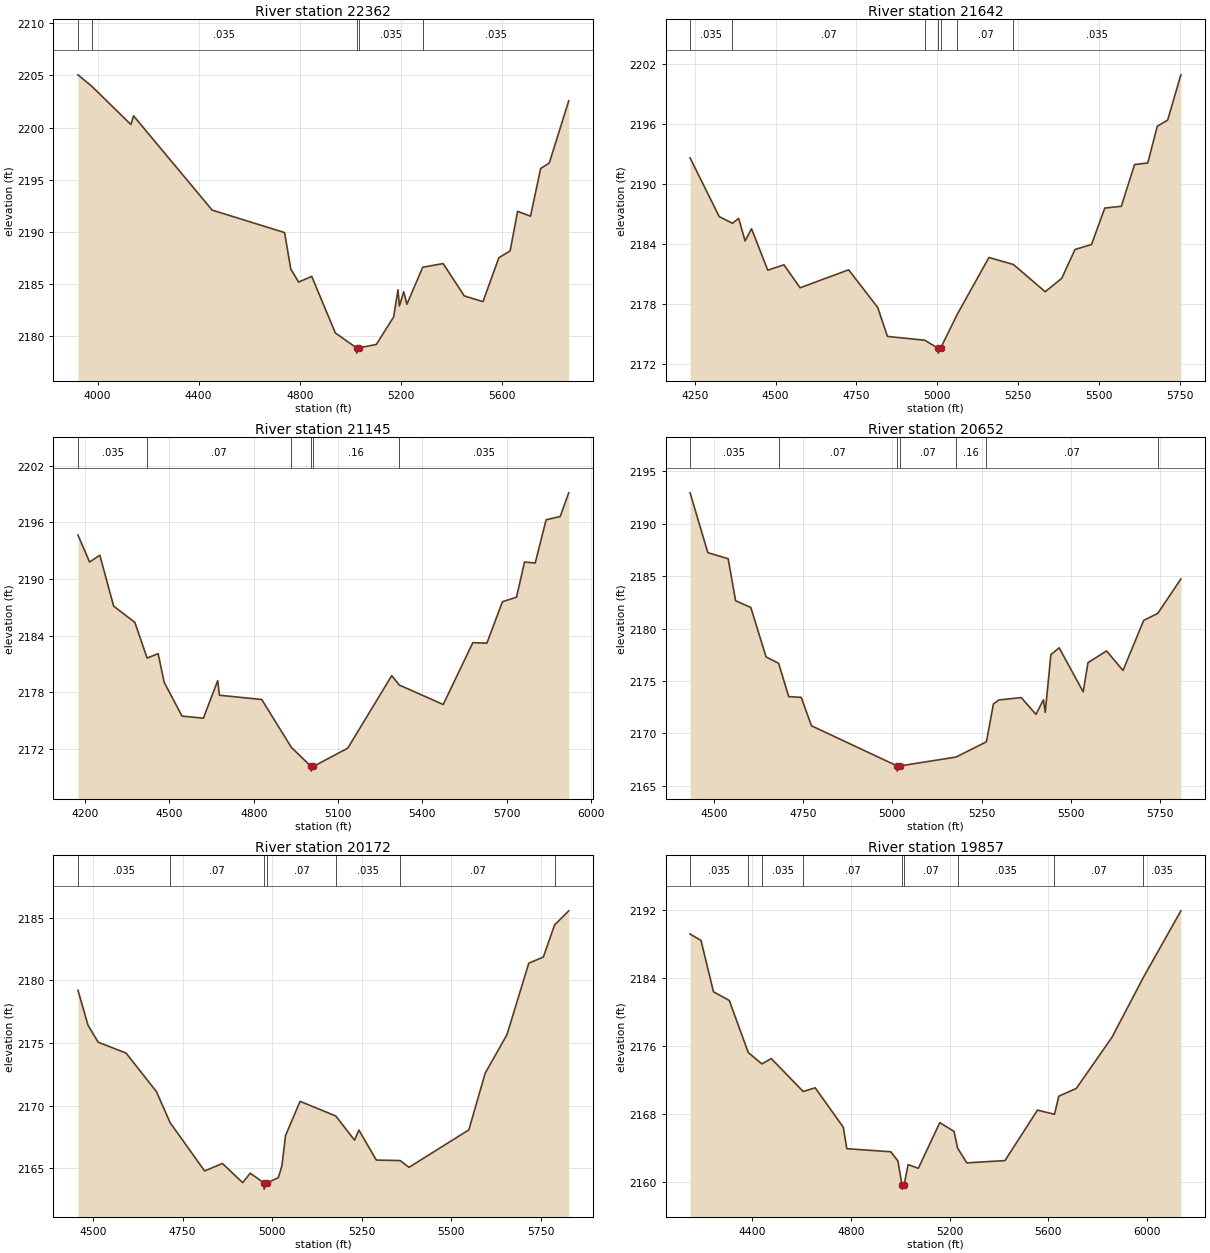
Type RM Length L Ch R = 1,22362,720,720,720
BEGIN DESCRIPTION:
Sweetwater Creek Trib 20 29.0
END DESCRIPTION:
XS GIS Cut Line= 3
      1385432.84      6829486.14      1386471.88      6829771.42
      1387255.03      6830138.01
#Sta/Elev= 30
  3922.5 2205.05  3976.1 2203.98  4132.1 2200.29  4142.5 2201.12  4453.6 2192.09
  4740.2 2189.94  4764.7 2186.45  4795.8 2185.20  4847.7 2185.74  4941.0 2180.33
  5025.0 2178.89  5025.5 2178.39  5033.3 2178.89  5103.2 2179.22  5171.7 2181.85
  5189.0 2184.46  5194.5 2182.91  5211.9 2184.27  5224.3 2183.07  5286.9 2186.62
  5367.8 2186.97  5451.2 2183.87  5525.3 2183.32  5588.3 2187.53  5632.8 2188.18
  5662.3 2191.97  5713.5 2191.51  5753.6 2196.08  5787.5 2196.59  5864.7 2202.56
#Mann=5,-1,0
  3922.5    0.07       0  3976.1   0.035       0  5025.0   0.035       0
  5033.3   0.035       0  5286.9   0.035       0
Bank Sta=5025,5033.3
Exp/Cntr=0.3,0.1

Type RM Length L Ch R = 1,21642,497,497,497
BEGIN DESCRIPTION:
Sweetwater Creek Trib 20 28.0
END DESCRIPTION:
XS GIS Cut Line= 3
      1385705.02      6830488.00      1386468.83      6830451.13
      1387204.97      6830288.01
#Sta/Elev= 30
  4235.3 2192.58  4325.4 2186.72  4366.4 2186.05  4385.5 2186.54  4405.5 2184.29
  4425.5 2185.50  4475.6 2181.36  4525.6 2181.90  4575.7 2179.60  4725.9 2181.40
  4816.0 2177.63  4846.0 2174.74  4961.4 2174.36  5002.2 2173.57  5002.7 2173.07
  5010.5 2173.57  5062.4 2176.97  5160.0 2182.63  5235.8 2181.93  5334.1 2179.21
  5385.3 2180.54  5426.3 2183.43  5477.5 2183.93  5518.5 2187.57  5569.7 2187.75
  5610.6 2191.92  5651.6 2192.08  5681.0 2195.75  5713.1 2196.37  5754.0 2200.89
#Mann=7,-1,0
  4235.3   0.035       0  4366.4    0.07       0  4961.4    0.16       0
  5002.2    0.07       0  5010.5    0.16       0  5062.4    0.07       0
  5235.8   0.035       0
Bank Sta=5002.2,5010.5
Exp/Cntr=0.3,0.1

Type RM Length L Ch R = 1,21145,493,493,493
BEGIN DESCRIPTION:
Sweetwater Creek Trib 20 27.0
END DESCRIPTION:
XS GIS Cut Line= 3
      1385655.00      6830638.00      1386435.08      6830908.03
      1387254.96      6830488.02
#Sta/Elev= 30
  4174.5 2194.67  4215.9 2191.81  4252.4 2192.53  4301.5 2187.14  4377.0 2185.41
  4420.7 2181.63  4459.9 2182.10  4481.4 2179.06  4544.9 2175.48  4621.0 2175.26
  4671.9 2179.24  4678.0 2177.69  4828.5 2177.24  4934.0 2172.17  5004.1 2170.15
  5004.6 2169.65  5012.4 2170.15  5134.7 2172.08  5291.3 2179.77  5318.3 2178.77
  5474.5 2176.71  5579.9 2183.26  5629.9 2183.21  5685.3 2187.60  5735.3 2188.08
  5763.9 2191.81  5801.9 2191.70  5840.7 2196.28  5890.8 2196.63  5921.2 2199.14
#Mann=6,-1,0
  4174.5   0.035       0  4420.7    0.07       0  4934.0    0.16       0
  5004.1    0.07       0  5012.4    0.16       0  5318.3   0.035       0
Bank Sta=5004.1,5012.4
Exp/Cntr=0.3,0.1

Type RM Length L Ch R = 1,20652,480,480,480
BEGIN DESCRIPTION:
Sweetwater Creek Trib 20 26.0
END DESCRIPTION:
XS GIS Cut Line= 3
      1385655.02      6830838.02      1386078.24      6831214.59
      1386855.05      6831438.01
#Sta/Elev= 30
  4433.5 2192.95  4483.2 2187.24  4540.1 2186.66  4561.0 2182.65  4603.6 2182.01
  4646.3 2177.29  4681.5 2176.68  4709.8 2173.50  4744.9 2173.43  4773.4 2170.72
  5013.2 2166.89  5013.7 2166.39  5021.7 2166.89  5178.2 2167.73  5263.6 2169.19
  5283.2 2172.80  5298.4 2173.18  5361.0 2173.41  5402.4 2171.81  5423.2 2173.20
  5428.4 2172.00  5444.1 2177.50  5467.3 2178.16  5534.7 2173.96  5548.1 2176.74
  5600.1 2177.86  5646.2 2176.00  5704.2 2180.78  5743.5 2181.44  5808.3 2184.73
#Mann=7,-1,0
  4433.5   0.035       0  4681.5    0.07       0  5013.2    0.07       0
  5021.7    0.07       0  5178.2    0.16       0  5263.6    0.07       0
  5743.5   0.035       0
Bank Sta=5013.2,5021.7
Exp/Cntr=0.3,0.1

Type RM Length L Ch R = 1,20172,315,315,315
BEGIN DESCRIPTION:
Sweetwater Creek Trib 20 25.0
END DESCRIPTION:
XS GIS Cut Line= 3
      1385654.97      6831237.97      1386038.24      6831621.48
      1386855.01      6831488.00
#Sta/Elev= 30
  4457.8 2179.21  4486.1 2176.40  4514.4 2175.06  4592.2 2174.19  4677.0 2171.11
  4715.0 2168.64  4811.4 2164.78  4860.9 2165.38  4917.5 2163.85  4938.7 2164.60
  4976.8 2163.83  4977.3 2163.33  4985.4 2163.83  5017.0 2164.24  5027.1 2165.19
  5037.2 2167.61  5077.8 2170.34  5177.3 2169.17  5229.8 2167.24  5241.8 2168.05
  5290.6 2165.65  5357.0 2165.61  5381.8 2165.07  5548.8 2168.06  5594.5 2172.59
  5655.3 2175.67  5716.1 2181.37  5756.7 2181.86  5788.1 2184.42  5827.6 2185.55
#Mann=7,-1,0
  4457.8   0.035       0  4715.0    0.07       0  4976.8    0.07       0
  4985.4    0.07       0  5177.3   0.035       0  5357.0    0.07       0
  5788.1   0.035       0
Bank Sta=4976.8,4985.4
Exp/Cntr=0.3,0.1

Type RM Length L Ch R = 1,19857,674,674,674
BEGIN DESCRIPTION:
Sweetwater Creek Trib 20 24.0
END DESCRIPTION:
XS GIS Cut Line= 3
      1385377.79      6831203.13      1385904.21      6831872.92
      1387005.03      6831587.99
#Sta/Elev= 30
  4148.1 2189.19  4192.4 2188.43  4242.9 2182.39  4306.9 2181.37  4384.0 2175.23
  4439.0 2173.90  4477.0 2174.53  4606.6 2170.65  4655.0 2171.09  4768.9 2166.45
  4783.3 2163.92  4961.4 2163.56  4990.3 2162.48  5006.8 2159.66  5007.3 2159.16
  5015.4 2159.66  5031.8 2162.05  5073.1 2161.61  5160.1 2166.99  5217.7 2165.96
  5232.3 2164.00  5269.4 2162.25  5424.3 2162.52  5555.9 2168.46  5624.9 2167.97
  5642.3 2170.10  5713.2 2171.01  5858.2 2177.05  5984.5 2184.05  6137.1 2191.92
#Mann=9,-1,0
  4148.1   0.035       0  4384.0    0.07       0  4439.0   0.035       0
  4606.6    0.07       0  5006.8    0.07       0  5015.4    0.07       0
  5232.3   0.035       0  5624.9    0.07       0  5984.5   0.035       0
Bank Sta=5006.8,5015.4
Exp/Cntr=0.3,0.1