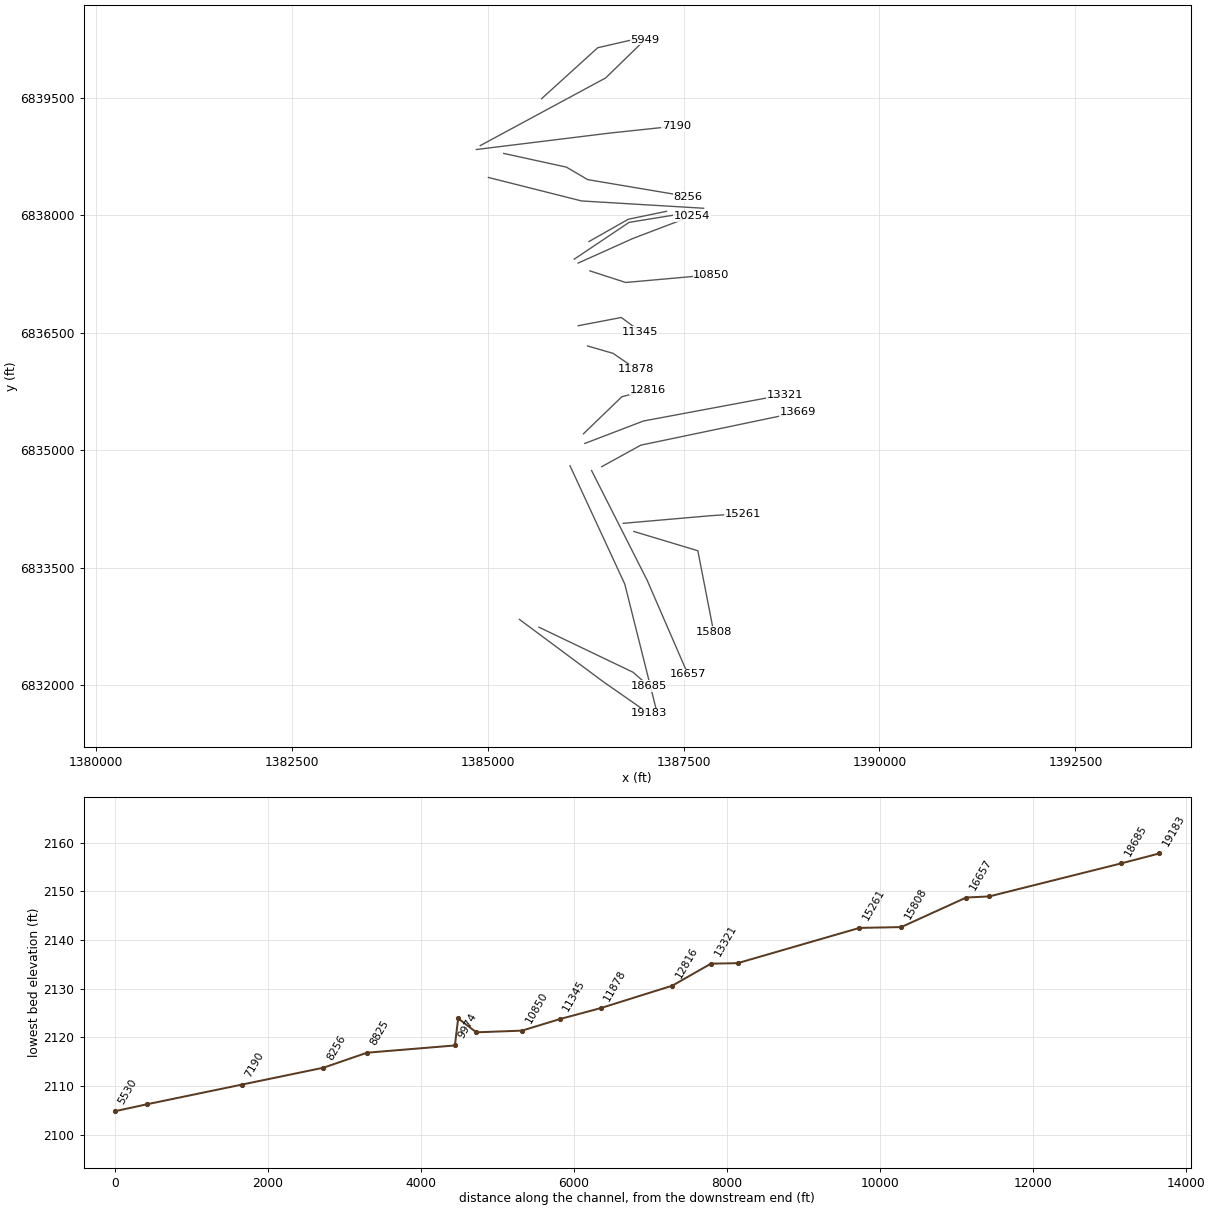
HEC-RAS study Sweetwater Creek Trib 20.prj: Sweetwater Creek Trib 20 Base Level Engineering

--- Sweetwater Creek Trib 20.g01 (geometry) --- (continued)

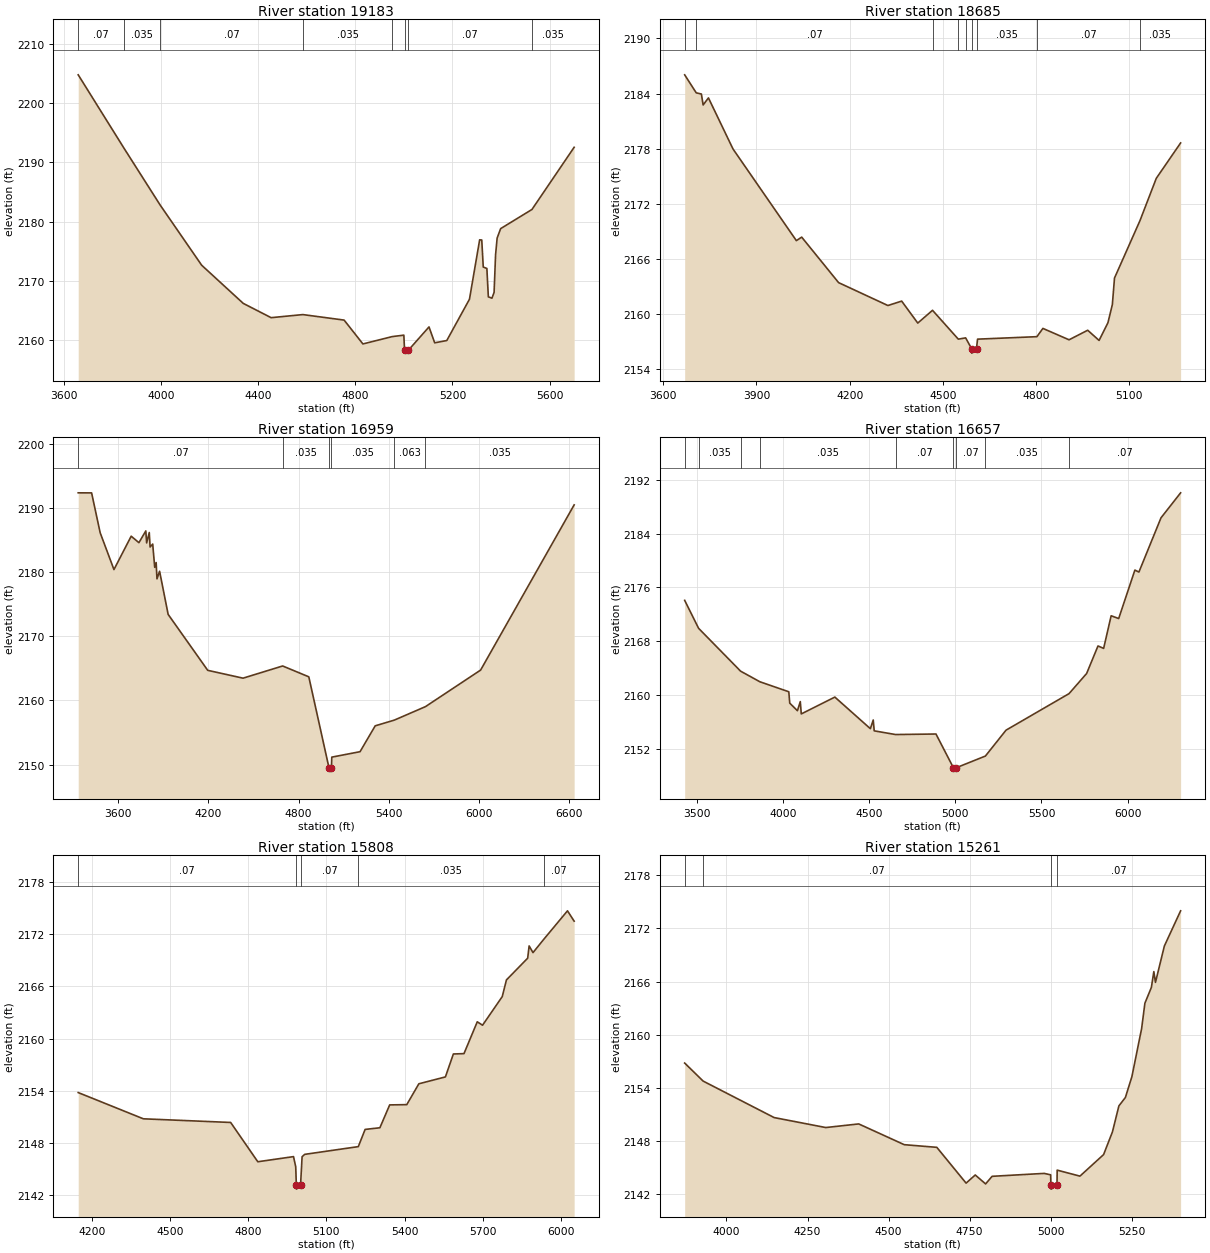
Type RM Length L Ch R = 1,19183,498,498,498
BEGIN DESCRIPTION:
Sweetwater Creek Trib 20 23.0
END DESCRIPTION:
XS GIS Cut Line= 3
      1385404.99      6832838.01      1386480.20      6832038.47
      1387055.04      6831637.97
#Sta/Elev= 30
  3660.1 2204.74  3848.4 2192.37  3997.7 2182.75  4168.0 2172.63  4339.1 2166.19
  4453.8 2163.78  4584.3 2164.30  4754.2 2163.37  4831.5 2159.35  4952.1 2160.59
  4999.9 2160.83  5002.8 2158.30  5003.3 2157.80  5018.8 2158.30  5103.4 2162.22
  5126.8 2159.54  5176.5 2159.92  5269.9 2166.89  5311.8 2176.91  5320.5 2176.88
  5326.6 2172.32  5341.5 2172.08  5347.6 2167.29  5362.4 2167.07  5371.2 2168.05
  5377.3 2174.37  5383.7 2177.20  5398.2 2178.80  5527.0 2182.03  5700.6 2192.52
#Mann=8,-1,0
  3660.1    0.07       0  3848.4   0.035       0  3997.7    0.07       0
  4584.3   0.035       0  4952.1    0.07       0  5002.8    0.07       0
  5018.8    0.07       0  5527.0   0.035       0
Bank Sta=5002.8,5018.8
Exp/Cntr=0.3,0.1

Type RM Length L Ch R = 1,18685,1726,1726,1726
BEGIN DESCRIPTION:
Sweetwater Creek Trib 20 22.0
END DESCRIPTION:
XS GIS Cut Line= 3
      1385655.03      6832737.98      1386855.43      6832162.99
      1387054.98      6831988.02
#Sta/Elev= 30
  3669.0 2186.04  3706.2 2184.08  3722.8 2183.95  3728.4 2182.76  3745.5 2183.53
  3824.6 2177.97  4028.5 2168.00  4045.7 2168.38  4164.5 2163.43  4323.1 2160.94
  4367.5 2161.42  4419.3 2159.03  4466.8 2160.42  4549.8 2157.28  4573.4 2157.42
  4592.4 2156.26  4592.9 2155.76  4608.4 2156.26  4611.7 2157.28  4802.8 2157.55
  4822.1 2158.45  4906.3 2157.21  4966.3 2158.25  5003.0 2157.14  5031.5 2159.07
  5045.7 2161.05  5052.6 2163.93  5134.5 2170.17  5187.1 2174.78  5265.4 2178.63
#Mann=9,-1,0
  3669.0   0.035       0  3706.2    0.07       0  4466.8    0.16       0
  4549.8    0.07       0  4573.4   0.035       0  4592.4    0.07       0
  4608.4   0.035       0  4802.8    0.07       0  5134.5   0.035       0
Bank Sta=4592.4,4608.4
Exp/Cntr=0.3,0.1

Type RM Length L Ch R = 1,16959,302,302,302
BEGIN DESCRIPTION:
Sweetwater Creek Trib 20 21.0
END DESCRIPTION:
XS GIS Cut Line= 3
      1386050.64      6834799.68      1386749.80      6833288.47
      1387146.85      6831704.68
#Sta/Elev= 30
  3334.9 2192.35  3424.0 2192.34  3480.9 2186.13  3572.6 2180.39  3687.2 2185.59
  3738.6 2184.58  3784.4 2186.41  3789.9 2184.54  3807.4 2186.16  3812.9 2183.91
  3830.3 2184.36  3843.6 2180.74  3853.2 2181.48  3858.7 2178.94  3876.1 2180.12
  3933.0 2173.40  4196.2 2164.68  4431.0 2163.46  4694.4 2165.36  4868.3 2163.67
  5002.7 2149.47  5003.2 2148.97  5018.8 2149.47  5021.1 2151.15  5209.1 2152.00
  5309.8 2156.03  5436.7 2156.92  5643.9 2159.02  6010.8 2164.72  6632.8 2190.47
#Mann=6,-1,0
  3334.9    0.07       0  4694.4   0.035       0  5002.7   0.035       0
  5018.8   0.035       0  5436.7   0.063       0  5643.9   0.035       0
Bank Sta=5002.7,5018.8
Exp/Cntr=0.3,0.1

Type RM Length L Ch R = 1,16657,849,849,849
BEGIN DESCRIPTION:
Sweetwater Creek Trib 20 20.0
END DESCRIPTION:
XS GIS Cut Line= 3
      1386325.72      6834739.34      1387034.95      6833337.98
      1387554.99      6832138.03
#Sta/Elev= 30
  3429.4 2174.09  3510.1 2169.94  3753.9 2163.58  3866.3 2162.00  4033.7 2160.52
  4039.3 2158.83  4083.8 2157.71  4100.5 2159.06  4106.1 2157.23  4301.0 2159.73
  4507.1 2155.04  4523.8 2156.33  4529.4 2154.72  4653.3 2154.17  4887.9 2154.25
  4989.1 2149.24  4989.6 2148.74  5005.2 2149.24  5174.9 2150.98  5294.5 2154.82
  5660.1 2160.24  5762.3 2163.23  5828.3 2167.32  5861.0 2166.96  5904.6 2171.80
  5948.4 2171.39  6042.3 2178.58  6065.8 2178.29  6194.0 2186.34  6307.8 2190.05
#Mann=9,-1,0
  3429.4    0.07       0  3510.1   0.035       0  3753.9    0.07       0
  3866.3   0.035       0  4653.3    0.07       0  4989.1    0.07       0
  5005.2    0.07       0  5174.9   0.035       0  5660.1    0.07       0
Bank Sta=4989.1,5005.2
Exp/Cntr=0.3,0.1

Type RM Length L Ch R = 1,15808,547,547,547
BEGIN DESCRIPTION:
Sweetwater Creek Trib 20 4175
END DESCRIPTION:
XS GIS Cut Line= 3
      1386865.59      6833960.67      1387681.99      6833714.53
      1387882.93      6832682.92
#Sta/Elev= 30
  4147.3 2153.78  4397.4 2150.76  4732.5 2150.34  4836.7 2145.82  4973.8 2146.41
  4982.3 2145.23  4984.5 2143.17  4985.0 2142.67  5000.8 2143.17  5006.7 2146.40
  5016.8 2146.67  5222.5 2147.56  5248.6 2149.54  5305.3 2149.73  5342.9 2152.36
  5408.5 2152.39  5454.9 2154.79  5556.8 2155.58  5587.4 2158.22  5628.1 2158.26
  5679.1 2161.92  5699.4 2161.53  5775.0 2164.82  5791.1 2166.74  5872.6 2169.24
  5878.2 2170.65  5893.0 2169.88  5935.7 2171.46  6025.4 2174.69  6051.0 2173.50
#Mann=5,-1,0
  4147.3    0.07       0  4984.5    0.07       0  5000.8    0.07       0
  5222.5   0.035       0  5935.7    0.07       0
Bank Sta=4984.5,5000.8
Exp/Cntr=0.3,0.1

Type RM Length L Ch R = 1,15261,1592,1592,1592
BEGIN DESCRIPTION:
Sweetwater Creek Trib 20 19.0
END DESCRIPTION:
XS GIS Cut Line= 3
      1386730.17      6834064.85      1387854.79      6834162.91
      1388255.02      6834188.00
#Sta/Elev= 30
  3871.1 2156.77  3928.0 2154.73  4147.0 2150.60  4306.4 2149.47  4408.0 2149.88
  4548.5 2147.53  4648.9 2147.23  4739.2 2143.18  4767.5 2144.10  4799.4 2143.09
  4819.5 2143.95  4980.1 2144.28  5000.0 2144.12  5000.8 2143.00  5001.3 2142.50
  5019.7 2143.00  5020.2 2144.65  5090.4 2143.97  5163.4 2146.41  5190.6 2148.97
  5210.6 2151.92  5230.6 2152.87  5250.7 2155.23  5280.7 2160.67  5290.8 2163.54
  5310.8 2165.33  5318.4 2167.12  5323.4 2165.90  5350.9 2170.02  5401.0 2174.00
#Mann=4,-1,0
  3871.1   0.035       0  3928.0    0.07       0  5000.8    0.07       0
  5019.7    0.07       0
Bank Sta=5000.8,5019.7
Exp/Cntr=0.3,0.1

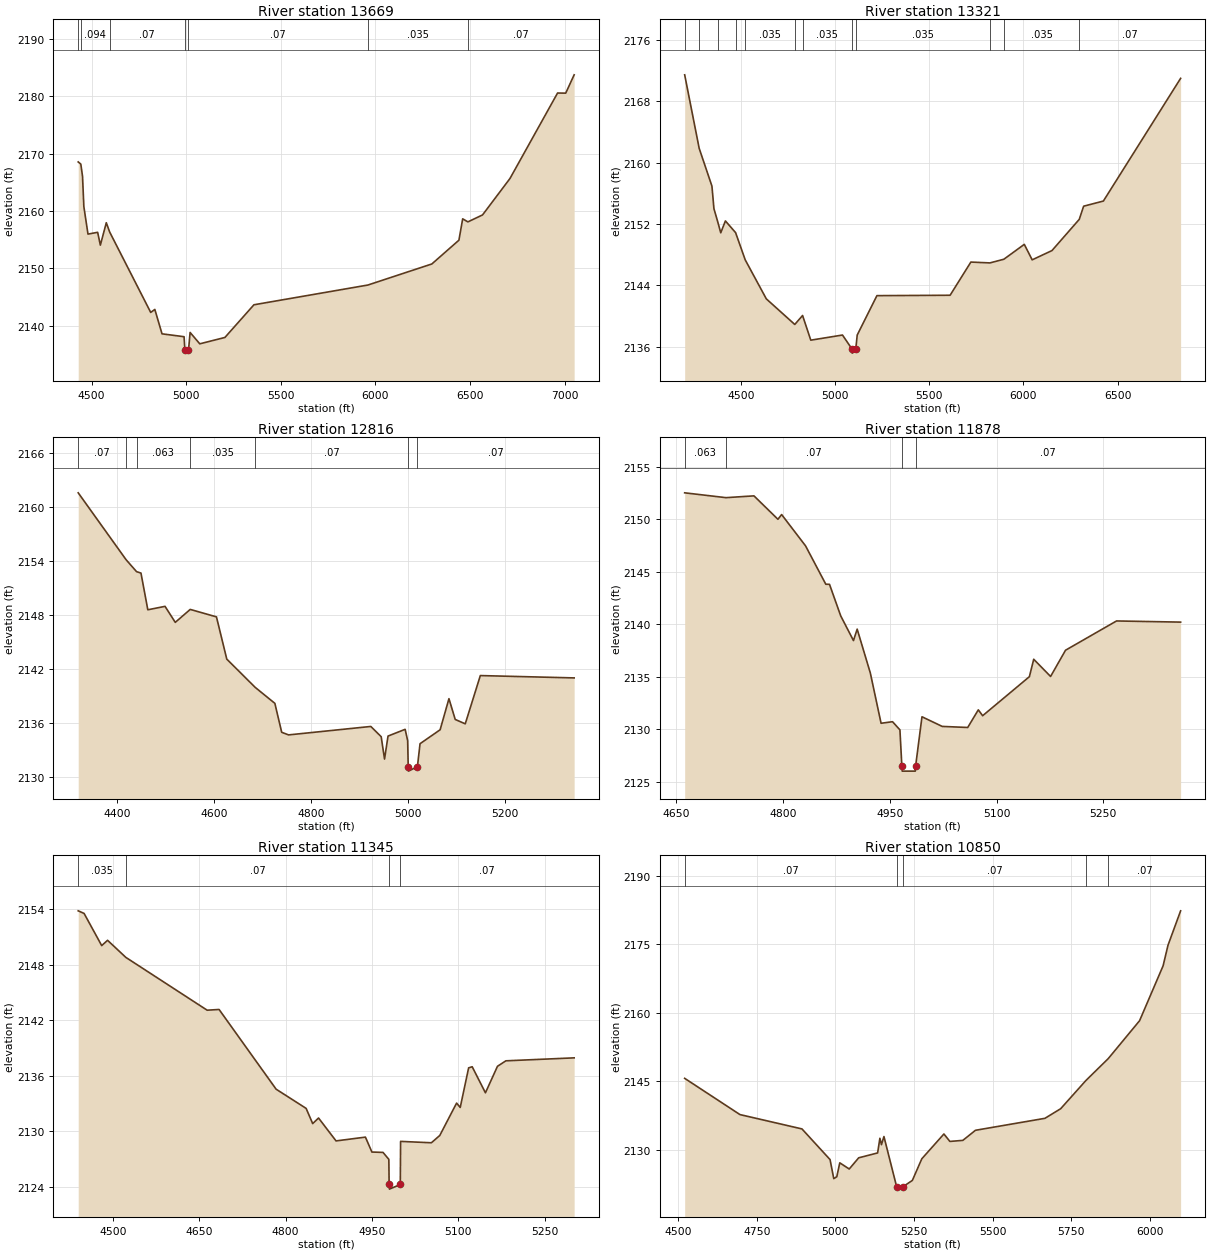
Type RM Length L Ch R = 1,13669,348,348,348
BEGIN DESCRIPTION:
Sweetwater Creek Trib 20 18.0
END DESCRIPTION:
XS GIS Cut Line= 3
      1386454.99      6834787.99      1386954.59      6835063.00
      1388960.77      6835482.68
#Sta/Elev= 30
  4429.7 2168.56  4443.4 2168.19  4452.5 2166.06  4459.5 2160.78  4481.3 2155.99
  4532.4 2156.30  4546.7 2154.07  4578.1 2157.97  4595.8 2156.36  4812.7 2142.35
  4834.5 2142.87  4872.4 2138.62  4989.0 2138.12  4993.3 2135.76  4993.8 2135.26
  5012.3 2135.76  5020.8 2138.86  5071.9 2136.88  5204.7 2137.99  5358.0 2143.68
  5960.1 2147.12  6297.9 2150.79  6440.9 2154.93  6460.7 2158.65  6488.4 2158.12
  6565.7 2159.33  6710.5 2165.67  6962.0 2180.56  7005.1 2180.54  7049.6 2183.73
#Mann=7,-1,0
  4429.7   0.035       0  4443.4   0.094       0  4595.8    0.07       0
  4993.3    0.07       0  5012.3    0.07       0  5960.1   0.035       0
  6488.4    0.07       0
Bank Sta=4993.3,5012.3
Exp/Cntr=0.3,0.1

Type RM Length L Ch R = 1,13321,505,505,505
BEGIN DESCRIPTION:
Sweetwater Creek Trib 20 17.0
END DESCRIPTION:
XS GIS Cut Line= 3
      1386239.70      6835084.86      1386987.72      6835371.29
      1388791.83      6835708.86
#Sta/Elev= 30
  4199.0 2171.47  4276.1 2161.88  4343.9 2156.95  4354.6 2154.00  4373.5 2152.40
  4390.8 2150.86  4415.5 2152.41  4469.7 2150.88  4520.8 2147.33  4633.0 2142.24
  4784.3 2138.90  4825.7 2140.07  4869.4 2136.85  5037.9 2137.52  5089.5 2135.66
  5090.0 2135.16  5108.5 2135.66  5116.1 2137.51  5221.0 2142.66  5610.0 2142.71
  5720.4 2147.04  5821.8 2146.93  5895.8 2147.41  6004.4 2149.35  6046.3 2147.33
  6151.5 2148.54  6296.5 2152.61  6319.8 2154.33  6424.8 2155.00  6835.4 2171.01
#Mann=12,-1,0
  4199.0    0.07       0  4276.1   0.035       0  4373.5   0.094       0
  4469.7   0.063       0  4520.8   0.035       0  4784.3    0.07       0
  4825.7   0.035       0  5089.5   0.035       0  5108.5   0.035       0
  5821.8    0.07       0  5895.8   0.035       0  6296.5    0.07       0
Bank Sta=5089.5,5108.5
Exp/Cntr=0.3,0.1

Type RM Length L Ch R = 1,12816,938,938,938
BEGIN DESCRIPTION:
Sweetwater Creek Trib 20 4453
END DESCRIPTION:
XS GIS Cut Line= 3
      1386222.07      6835207.83      1386711.19      6835680.24
      1387041.64      6835769.91
#Sta/Elev= 30
  4320.0 2161.60  4418.7 2154.16  4440.3 2152.83  4449.4 2152.67  4463.5 2148.59
  4499.0 2148.97  4520.1 2147.19  4550.9 2148.63  4605.0 2147.80  4626.3 2143.10
  4684.8 2139.96  4725.4 2138.18  4739.5 2134.96  4753.7 2134.67  4923.2 2135.61
  4944.6 2134.47  4951.5 2131.98  4958.7 2134.54  4994.0 2135.29  4999.2 2134.03
  5000.3 2131.14  5000.8 2130.64  5019.3 2131.14  5024.7 2133.69  5066.1 2135.24
  5084.3 2138.70  5097.2 2136.39  5117.9 2135.90  5149.0 2141.27  5342.4 2141.01
#Mann=7,-1,0
  4320.0    0.07       0  4418.7   0.035       0  4440.3   0.063       0
  4550.9   0.035       0  4684.8    0.07       0  5000.3    0.07       0
  5019.3    0.07       0
Bank Sta=5000.3,5019.3
Exp/Cntr=0.3,0.1

Type RM Length L Ch R = 1,11878,533,533,533
BEGIN DESCRIPTION:
Sweetwater Creek Trib 20 4452
END DESCRIPTION:
XS GIS Cut Line= 3
      1386274.23      6836329.37      1386599.48      6836235.58
      1386895.33      6836032.77
#Sta/Elev= 30
  4661.5 2152.54  4719.5 2152.08  4758.9 2152.25  4792.6 2150.02  4797.8 2150.47
  4831.4 2147.49  4859.9 2143.83  4865.1 2143.82  4880.9 2140.81  4898.8 2138.46
  4904.0 2139.55  4922.5 2135.37  4937.6 2130.58  4953.7 2130.73  4964.1 2129.95
  4966.8 2126.52  4967.3 2126.02  4985.7 2126.02  4986.2 2126.52  4995.1 2131.20
  5023.6 2130.28  5059.4 2130.18  5074.3 2131.86  5080.4 2131.30  5146.1 2135.02
  5152.2 2136.68  5175.9 2135.04  5196.9 2137.54  5268.6 2140.33  5358.7 2140.22
#Mann=4,-1,0
  4661.5   0.063       0  4719.5    0.07       0  4966.8    0.07       0
  4986.2    0.07       0
Bank Sta=4966.8,4986.2
Exp/Cntr=0.3,0.1

Type RM Length L Ch R = 1,11345,495,495,495
BEGIN DESCRIPTION:
Sweetwater Creek Trib 20 13.0
END DESCRIPTION:
XS GIS Cut Line= 3
      1386154.95      6836587.99      1386705.38      6836693.16
      1386947.28      6836513.84
#Sta/Elev= 30
  4439.6 2153.79  4449.8 2153.51  4480.4 2150.04  4490.6 2150.61  4522.3 2148.77
  4663.6 2143.07  4684.3 2143.15  4783.4 2134.55  4835.5 2132.48  4846.9 2130.84
  4857.1 2131.44  4887.5 2128.97  4938.5 2129.38  4949.8 2127.77  4969.1 2127.73
  4979.2 2126.98  4979.7 2124.27  4980.2 2123.77  4999.1 2124.27  4999.6 2128.92
  5053.1 2128.77  5067.7 2129.56  5096.9 2133.05  5103.2 2132.58  5117.8 2136.85
  5124.0 2136.97  5147.0 2134.16  5167.9 2137.02  5182.5 2137.61  5301.1 2137.93
#Mann=4,-1,0
  4439.6   0.035       0  4522.3    0.07       0  4979.7    0.07       0
  4999.1    0.07       0
Bank Sta=4979.7,4999.1
Exp/Cntr=0.3,0.1

Type RM Length L Ch R = 1,10850,596,596,596
BEGIN DESCRIPTION:
Sweetwater Creek Trib 20 12.0
END DESCRIPTION:
XS GIS Cut Line= 3
      1386305.04      6837287.99      1386761.07      6837140.20
      1387855.02      6837238.00
#Sta/Elev= 30
  4520.6 2145.67  4696.5 2137.73  4893.7 2134.59  4983.1 2127.87  4994.9 2123.70
  5004.5 2124.11  5014.0 2127.16  5044.1 2125.81  5074.2 2128.26  5134.4 2129.33
  5141.6 2132.54  5146.6 2131.14  5154.5 2132.92  5195.0 2121.90  5195.5 2121.40
  5214.5 2121.90  5244.9 2123.31  5275.0 2128.05  5345.3 2133.48  5364.3 2131.85
  5405.5 2132.08  5445.7 2134.29  5666.6 2136.91  5716.8 2139.02  5797.2 2145.21
  5867.9 2149.98  5967.8 2158.30  6042.6 2170.33  6058.1 2174.82  6098.3 2182.37
#Mann=5,-1,0
  4520.6    0.07       0  5195.0    0.07       0  5214.5    0.07       0
  5797.2   0.035       0  5867.9    0.07       0
Bank Sta=5195,5214.5
Exp/Cntr=0.3,0.1

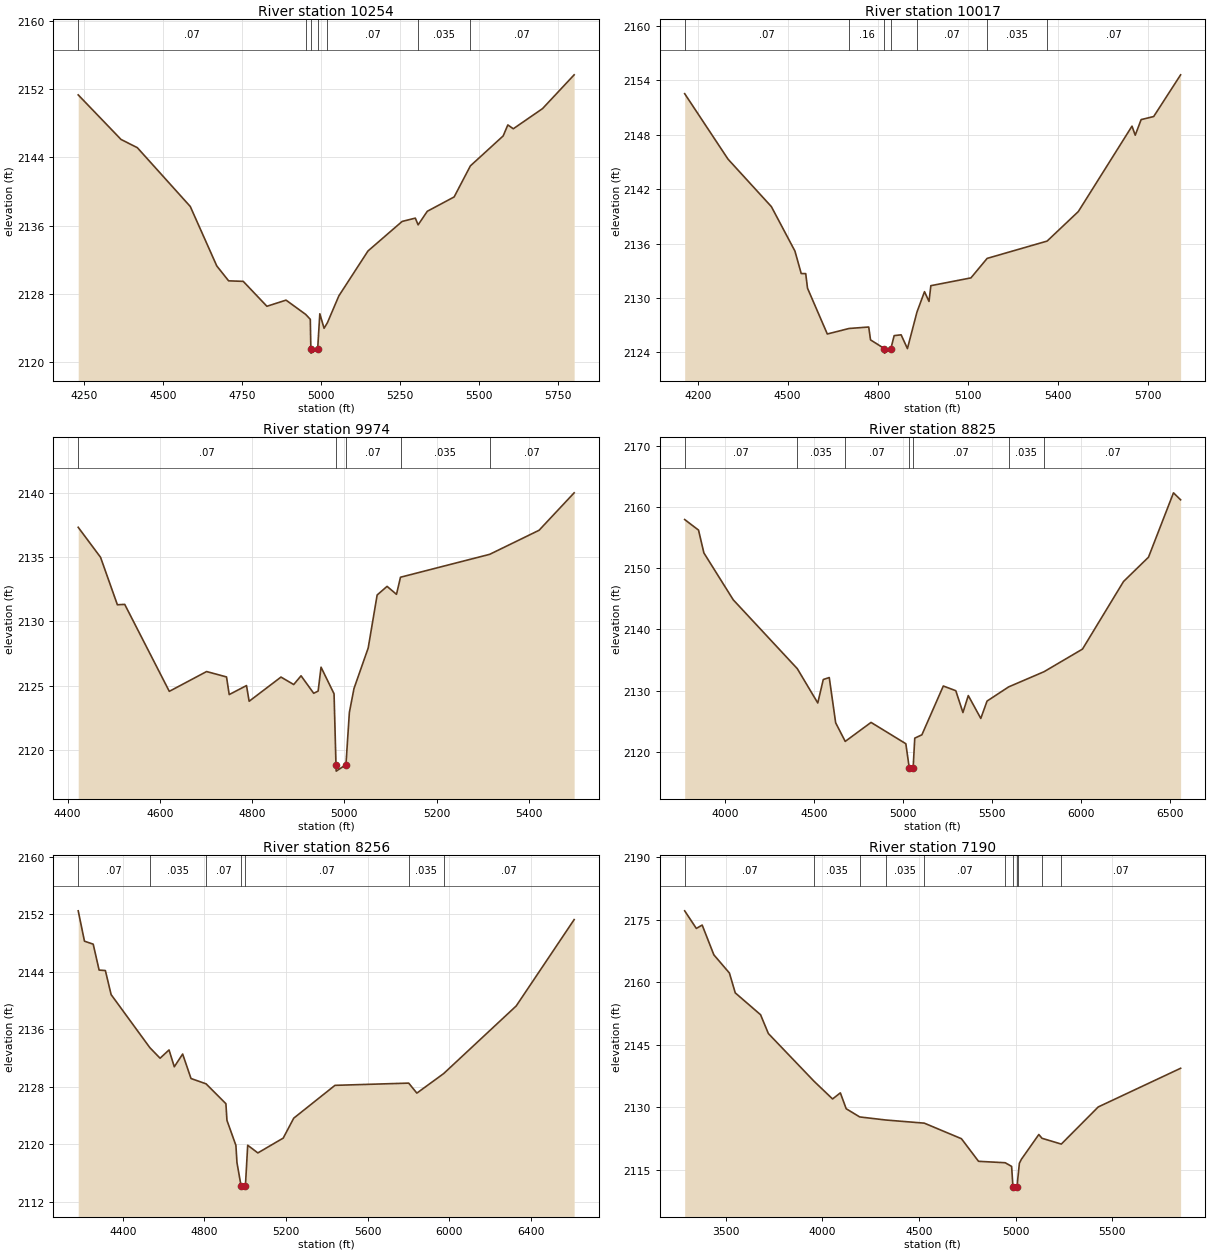
Type RM Length L Ch R = 1,10254,237,237,237
BEGIN DESCRIPTION:
Sweetwater Creek Trib 20 11.0
END DESCRIPTION:
XS GIS Cut Line= 3
      1386155.03      6837388.02      1386855.02      6837703.02
      1387605.00      6837988.00
#Sta/Elev= 30
  4232.4 2151.32  4367.9 2146.10  4419.7 2145.13  4587.2 2138.24  4671.0 2131.28
  4708.5 2129.53  4754.8 2129.47  4829.7 2126.55  4890.3 2127.27  4952.4 2125.60
  4967.1 2125.02  4968.8 2121.56  4969.3 2121.06  4990.4 2121.56  4997.2 2125.67
  5010.7 2123.97  5021.2 2124.62  5057.5 2127.77  5149.7 2133.03  5257.7 2136.49
  5299.5 2136.88  5308.4 2136.09  5337.4 2137.68  5422.4 2139.36  5473.8 2143.00
  5577.6 2146.51  5592.4 2147.80  5609.7 2147.35  5702.2 2149.71  5802.3 2153.67
#Mann=7,-1,0
  4232.4    0.07       0  4952.4    0.16       0  4968.8    0.07       0
  4990.4    0.16       0  5021.2    0.07       0  5308.4   0.035       0
  5473.8    0.07       0
Bank Sta=4968.8,4990.4
Exp/Cntr=0.3,0.1

Type RM Length L Ch R = 1,10017,43,43,43
BEGIN DESCRIPTION:
Sweetwater Creek Trib 20 10.0
END DESCRIPTION:
XS GIS Cut Line= 3
      1386104.98      6837437.99      1386805.12      6837907.87
      1387605.01      6838038.00
#Sta/Elev= 30
  4156.8 2152.53  4301.3 2145.31  4445.9 2140.07  4524.4 2135.17  4545.4 2132.69
  4560.4 2132.68  4566.4 2131.07  4632.4 2126.02  4705.0 2126.63  4770.5 2126.79
  4776.5 2125.37  4822.7 2124.41  4823.2 2123.91  4844.3 2124.41  4855.3 2125.84
  4878.5 2125.93  4899.5 2124.41  4931.3 2128.44  4956.5 2130.69  4971.5 2129.61
  4977.6 2131.35  5111.3 2132.21  5165.3 2134.36  5365.3 2136.27  5469.4 2139.53
  5648.3 2148.95  5659.1 2147.95  5678.7 2149.67  5720.6 2150.01  5810.4 2154.61
#Mann=7,-1,0
  4156.8    0.07       0  4705.0    0.16       0  4822.7    0.07       0
  4844.3    0.16       0  4931.3    0.07       0  5165.3   0.035       0
  5365.3    0.07       0
Bank Sta=4822.7,4844.3
Exp/Cntr=0.3,0.1

Type RM Length L Ch R = 1,9974,1149,1149,1149
BEGIN DESCRIPTION:
Sweetwater Creek Trib 20 4146
END DESCRIPTION:
XS GIS Cut Line= 3
      1386292.91      6837662.90      1386794.47      6837947.75
      1387281.98      6838048.95
#Sta/Elev= 30
  4423.2 2137.31  4471.6 2134.98  4508.1 2131.29  4524.0 2131.32  4620.6 2124.56
  4701.4 2126.10  4744.6 2125.68  4750.4 2124.31  4787.9 2125.01  4793.6 2123.79
  4862.6 2125.67  4890.2 2125.09  4906.1 2125.77  4933.5 2124.41  4943.1 2124.58
  4949.4 2126.44  4977.6 2124.37  4981.8 2118.86  4982.3 2118.36  5003.4 2118.86
  5010.8 2122.92  5020.8 2124.78  5051.6 2127.93  5071.0 2132.05  5092.5 2132.72
  5112.9 2132.10  5121.6 2133.43  5314.9 2135.21  5421.9 2137.08  5497.9 2139.99
#Mann=5,-1,0
  4423.2    0.07       0  4981.8    0.07       0  5003.4    0.07       0
  5121.6   0.035       0  5314.9    0.07       0
Bank Sta=4981.8,5003.4
Exp/Cntr=0.3,0.1

Type RM Length L Ch R = 1,8825,569,569,569
BEGIN DESCRIPTION:
Sweetwater Creek Trib 20 9.0
END DESCRIPTION:
XS GIS Cut Line= 3
      1385010.42      6838480.95      1386198.51      6838181.28
      1387755.02      6838088.00
#Sta/Elev= 30
  3774.7 2157.92  3852.4 2156.20  3882.6 2152.47  4047.5 2144.82  4407.0 2133.59
  4522.0 2127.99  4552.9 2131.82  4586.5 2132.14  4622.5 2124.75  4676.2 2121.72
  4821.1 2124.82  5016.5 2121.34  5035.8 2117.37  5036.3 2116.87  5057.4 2117.37
  5066.6 2122.25  5106.7 2122.80  5226.9 2130.76  5297.0 2129.99  5337.1 2126.43
  5367.1 2129.20  5437.3 2125.47  5472.5 2128.30  5593.4 2130.61  5792.9 2133.10
  6008.3 2136.78  6238.7 2147.81  6379.0 2151.78  6519.2 2162.28  6559.3 2161.14
#Mann=7,-1,0
  3774.7    0.07       0  4407.0   0.035       0  4676.2    0.07       0
  5035.8    0.07       0  5057.4    0.07       0  5593.4   0.035       0
  5792.9    0.07       0
Bank Sta=5035.8,5057.4
Exp/Cntr=0.3,0.1

Type RM Length L Ch R = 1,8256,1066,1066,1066
BEGIN DESCRIPTION:
Sweetwater Creek Trib 20 8.0
END DESCRIPTION:
XS GIS Cut Line= 4
      1385204.98      6838788.00      1386004.50      6838613.24
      1386275.96      6838453.68      1387555.02      6838238.00
#Sta/Elev= 30
  4181.6 2152.46  4212.3 2148.24  4255.1 2147.83  4284.0 2144.23  4314.7 2144.16
  4342.9 2140.82  4532.6 2133.45  4582.8 2131.98  4626.7 2133.13  4652.5 2130.79
  4693.4 2132.56  4734.4 2129.16  4808.3 2128.42  4905.4 2125.66  4910.5 2123.35
  4954.4 2119.87  4959.6 2117.48  4979.4 2114.29  4979.9 2113.79  5001.1 2114.29
  5012.2 2119.89  5062.0 2118.82  5186.2 2120.88  5237.8 2123.65  5439.9 2128.21
  5801.3 2128.52  5841.2 2127.13  5972.3 2129.84  6328.0 2139.24  6612.0 2151.24
#Mann=7,-1,0
  4181.6    0.07       0  4532.6   0.035       0  4808.3    0.07       0
  4979.4    0.07       0  5001.1    0.07       0  5801.3   0.035       0
  5972.3    0.07       0
Bank Sta=4979.4,5001.1
Exp/Cntr=0.3,0.1

Type RM Length L Ch R = 1,7190,1241,1241,1241
BEGIN DESCRIPTION:
Sweetwater Creek Trib 20 7.0
END DESCRIPTION:
XS GIS Cut Line= 3
      1384855.05      6838838.01      1386555.37      6839047.66
      1387404.98      6839138.00
#Sta/Elev= 30
  3286.8 2177.17  3347.2 2172.94  3377.4 2173.75  3437.9 2166.60  3518.5 2162.22
  3548.7 2157.46  3679.7 2152.21  3720.0 2147.70  3956.8 2136.22  4052.5 2131.98
  4092.8 2133.44  4123.0 2129.63  4193.0 2127.66  4328.5 2126.92  4527.3 2126.17
  4719.7 2122.43  4808.2 2117.00  4946.2 2116.66  4979.5 2115.78  4986.3 2110.82
  4986.8 2110.32  5008.2 2110.82  5010.1 2112.22  5019.7 2116.54  5029.8 2117.47
  5120.3 2123.44  5136.9 2122.53  5236.7 2121.14  5427.9 2130.06  5854.4 2139.35
#Mann=11,-1,0
  3286.8    0.07       0  3956.8   0.035       0  4193.0    0.07       0
  4328.5   0.035       0  4527.3    0.07       0  4946.2    0.16       0
  4986.3    0.07       0  5008.2    0.16       0  5010.1    0.07       0
  5136.9   0.035       0  5236.7    0.07       0
Bank Sta=4986.3,5008.2
Exp/Cntr=0.3,0.1

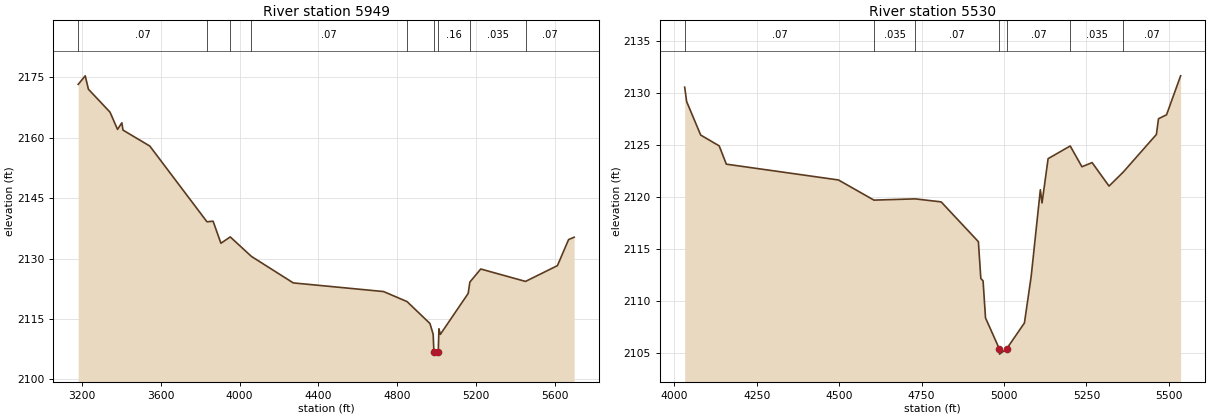
Type RM Length L Ch R = 1,5949,419,419,419
BEGIN DESCRIPTION:
Sweetwater Creek Trib 20 6.0
END DESCRIPTION:
XS GIS Cut Line= 3
      1384905.04      6838888.02      1386505.13      6839751.69
      1387005.00      6840238.00
#Sta/Elev= 30
  3181.7 2173.28  3217.3 2175.40  3233.5 2172.07  3343.0 2166.38  3381.1 2162.10
  3403.0 2163.73  3408.9 2161.92  3544.8 2157.96  3834.9 2139.15  3865.9 2139.30
  3905.6 2133.82  3952.9 2135.39  4060.6 2130.54  4272.6 2123.97  4730.9 2121.82
  4850.0 2119.32  4966.0 2113.88  4982.3 2111.19  4986.1 2106.78  4986.6 2106.28
  5008.0 2106.78  5011.5 2112.57  5018.5 2111.18  5159.9 2121.36  5168.4 2124.17
  5223.5 2127.42  5450.8 2124.34  5612.6 2128.26  5669.2 2134.73  5697.4 2135.32
#Mann=9,-1,0
  3181.7    0.07       0  3834.9   0.063       0  3952.9   0.035       0
  4060.6    0.07       0  4850.0    0.16       0  4986.1    0.07       0
  5008.0    0.16       0  5168.4   0.035       0  5450.8    0.07       0
Bank Sta=4986.1,5008
Exp/Cntr=0.3,0.1

Type RM Length L Ch R = 1,5530,167,167,167
BEGIN DESCRIPTION:
Sweetwater Creek Trib 20 4063
END DESCRIPTION:
XS GIS Cut Line= 3
      1385687.79      6839486.94      1386404.67      6840137.86
      1386926.58      6840257.73
#Sta/Elev= 30
  4031.7 2130.54  4037.7 2129.15  4080.3 2125.93  4136.4 2124.89  4158.0 2123.13
  4497.9 2121.61  4605.6 2119.67  4730.6 2119.79  4809.4 2119.50  4922.3 2115.67
  4929.7 2112.13  4936.5 2111.90  4943.9 2108.34  4985.9 2105.35  4986.4 2104.85
  5007.8 2105.35  5061.9 2107.85  5082.4 2112.34  5110.2 2120.67  5115.3 2119.40
  5133.7 2123.66  5200.7 2124.88  5236.3 2122.88  5267.1 2123.28  5318.4 2121.02
  5361.0 2122.35  5462.1 2125.99  5468.4 2127.50  5492.8 2127.88  5535.5 2131.63
#Mann=7,-1,0
  4031.7    0.07       0  4605.6   0.035       0  4730.6    0.07       0
  4985.9    0.07       0  5007.8    0.07       0  5200.7   0.035       0
  5361.0    0.07       0
Bank Sta=4985.9,5007.8
Exp/Cntr=0.3,0.1