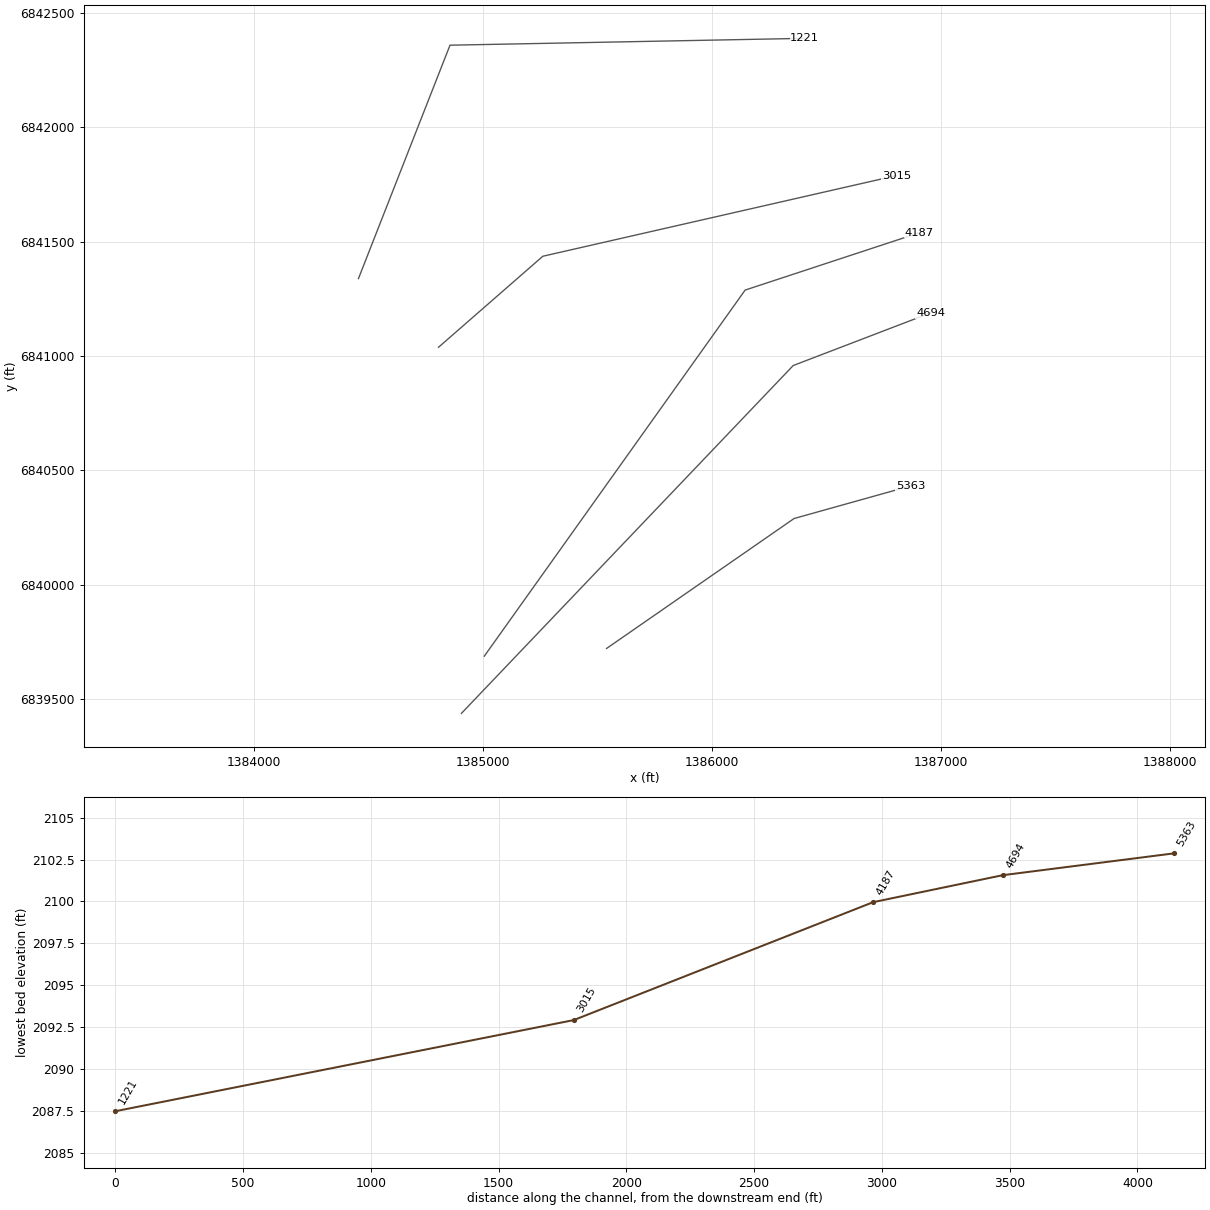
HEC-RAS study Sweetwater Creek Trib 20.prj: Sweetwater Creek Trib 20 Base Level Engineering

--- Sweetwater Creek Trib 20.g01 (geometry) --- (continued)

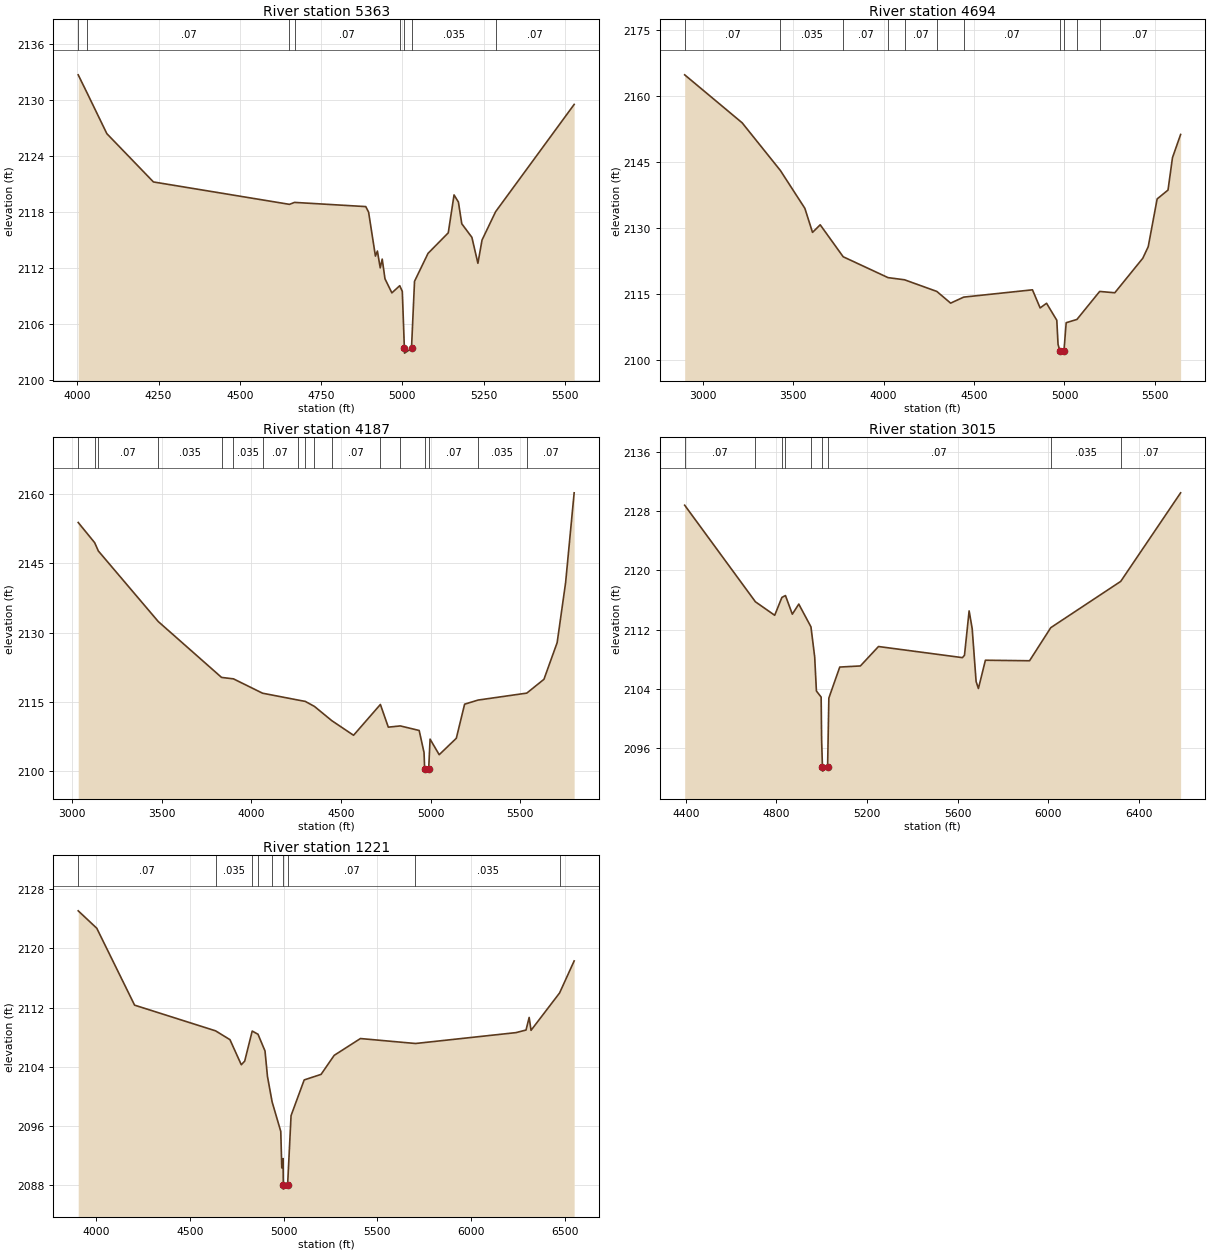
Type RM Length L Ch R = 1,5363,669,669,669
BEGIN DESCRIPTION:
Sweetwater Creek Trib 20 5.0
END DESCRIPTION:
XS GIS Cut Line= 3
      1385539.24      6839721.62      1386358.78      6840289.57
      1386867.96      6840431.92
#Sta/Elev= 30
  4002.9 2132.67  4030.8 2130.69  4091.0 2126.37  4234.3 2121.20  4652.9 2118.80
  4668.4 2119.01  4887.6 2118.56  4896.3 2117.97  4917.3 2113.26  4923.4 2113.80
  4932.1 2112.00  4938.2 2112.94  4946.7 2110.83  4967.9 2109.32  4992.1 2110.09
  5000.0 2109.48  5006.4 2103.37  5006.9 2102.87  5028.3 2103.37  5037.6 2110.56
  5079.1 2113.55  5141.4 2115.75  5159.2 2119.81  5172.6 2119.05  5183.0 2116.72
  5214.1 2115.27  5232.6 2112.49  5245.3 2114.98  5287.0 2118.01  5528.7 2129.50
#Mann=8,-1,0
  4002.9   0.035       0  4030.8    0.07       0  4652.9   0.035       0
  4668.4    0.07       0  4992.1   0.035       0  5006.4   0.035       0
  5028.3   0.035       0  5287.0    0.07       0
Bank Sta=5006.4,5028.3
Exp/Cntr=0.3,0.1

Type RM Length L Ch R = 1,4694,507,507,507
BEGIN DESCRIPTION:
Sweetwater Creek Trib 20 4.0
END DESCRIPTION:
XS GIS Cut Line= 3
      1384905.00      6839438.00      1386355.01      6840958.14
      1386954.99      6841188.00
#Sta/Elev= 30
  2899.2 2164.87  3217.3 2153.95  3428.6 2143.11  3563.9 2134.51  3606.4 2129.03
  3648.9 2130.76  3775.9 2123.49  4024.3 2118.74  4115.4 2118.25  4294.1 2115.60
  4370.4 2112.94  4442.5 2114.31  4823.0 2115.97  4865.4 2111.85  4901.0 2112.91
  4957.6 2109.04  4964.5 2103.57  4974.7 2102.07  4975.2 2101.57  4997.2 2102.07
  5009.5 2108.49  5068.9 2109.23  5194.7 2115.60  5278.4 2115.30  5433.3 2123.15
  5463.3 2125.78  5512.7 2136.64  5572.8 2138.66  5597.5 2146.03  5642.5 2151.30
#Mann=11,-1,0
  2899.2    0.07       0  3428.6   0.035       0  3775.9    0.07       0
  4024.3   0.035       0  4115.4    0.07       0  4294.1   0.035       0
  4442.5    0.07       0  4974.7    0.07       0  4997.2    0.07       0
  5068.9   0.035       0  5194.7    0.07       0
Bank Sta=4974.7,4997.2
Exp/Cntr=0.3,0.1

Type RM Length L Ch R = 1,4187,1172,1172,1172
BEGIN DESCRIPTION:
Sweetwater Creek Trib 20 3.0
END DESCRIPTION:
XS GIS Cut Line= 3
      1385004.98      6839687.98      1386144.95      6841287.89
      1386904.96      6841537.99
#Sta/Elev= 30
  3035.5 2153.85  3127.3 2149.47  3147.7 2147.68  3481.5 2132.39  3834.6 2120.27
  3900.9 2119.96  4063.1 2116.85  4259.0 2115.38  4301.4 2115.07  4352.2 2113.99
  4449.1 2110.90  4570.4 2107.73  4720.0 2114.41  4764.1 2109.49  4831.1 2109.76
  4936.2 2108.77  4963.3 2103.99  4966.7 2100.46  4967.2 2099.96  4989.2 2100.46
  4997.0 2106.89  5047.9 2103.52  5143.2 2107.08  5189.5 2114.47  5264.3 2115.36
  5536.1 2116.87  5631.7 2119.86  5705.4 2127.82  5752.5 2140.82  5800.1 2160.28
#Mann=17,-1,0
  3035.5    0.07       0  3127.3   0.035       0  3147.7    0.07       0
  3481.5   0.035       0  3834.6    0.07       0  3900.9   0.035       0
  4063.1    0.07       0  4259.0   0.035       0  4301.4    0.07       0
  4352.2   0.035       0  4449.1    0.07       0  4720.0   0.035       0
  4831.1    0.07       0  4966.7    0.07       0  4989.2    0.07       0
  5264.3   0.035       0  5536.1    0.07       0
Bank Sta=4966.7,4989.2
Exp/Cntr=0.3,0.1

Type RM Length L Ch R = 1,3015,1794,1794,1794
BEGIN DESCRIPTION:
Sweetwater Creek Trib 20 2.0
END DESCRIPTION:
XS GIS Cut Line= 3
      1384805.02      6841038.02      1385260.81      6841435.71
      1386805.03      6841788.01
#Sta/Elev= 30
  4395.1 2128.77  4707.3 2115.75  4792.4 2113.93  4824.2 2116.34  4839.9 2116.59
  4870.2 2114.08  4898.7 2115.44  4952.4 2112.37  4968.9 2108.31  4976.5 2103.72
  4997.4 2102.90  4999.5 2097.10  5003.2 2093.42  5003.7 2092.92  5025.9 2093.42
  5031.4 2102.77  5079.5 2106.95  5170.6 2107.10  5250.5 2109.72  5621.0 2108.22
  5630.0 2108.54  5650.5 2114.52  5664.0 2112.14  5681.3 2105.00  5691.5 2104.06
  5722.3 2107.87  5917.2 2107.80  6010.8 2112.26  6319.5 2118.50  6583.9 2130.44
#Mann=9,-1,0
  4395.1    0.07       0  4707.3   0.035       0  4824.2   0.063       0
  4839.9   0.035       0  4952.4    0.07       0  5003.2    0.07       0
  5025.9    0.07       0  6010.8   0.035       0  6319.5    0.07       0
Bank Sta=5003.2,5025.9
Exp/Cntr=0.3,0.1

Type RM Length L Ch R = 1,1221,0,0,0
BEGIN DESCRIPTION:
Sweetwater Creek Trib 20 1634
END DESCRIPTION:
XS GIS Cut Line= 3
      1384454.99      6841337.98      1384855.07      6842358.03
      1386404.98      6842388.00
#Sta/Elev= 30
  3904.3 2125.07  4003.3 2122.72  4205.1 2112.33  4637.1 2108.86  4713.8 2107.67
  4774.4 2104.28  4792.5 2104.77  4832.6 2108.83  4863.5 2108.40  4900.9 2106.14
  4914.0 2102.70  4938.9 2099.26  4985.0 2095.27  4990.4 2090.34  4997.3 2091.61
  4998.6 2087.98  4999.1 2087.48  5021.3 2087.98  5039.9 2097.41  5109.9 2102.23
  5200.0 2102.98  5270.0 2105.55  5410.0 2107.82  5703.7 2107.15  6240.2 2108.62
  6293.4 2108.97  6310.2 2110.67  6320.2 2108.93  6472.3 2113.97  6550.2 2118.30
#Mann=9,-1,0
  3904.3    0.07       0  4637.1   0.035       0  4832.6   0.063       0
  4863.5   0.035       0  4938.9    0.07       0  4998.6    0.07       0
  5021.3    0.07       0  5703.7   0.035       0  6472.3    0.07       0
Bank Sta=4998.6,5021.3
Exp/Cntr=0.3,0.1

Chan Stop Cuts=-1