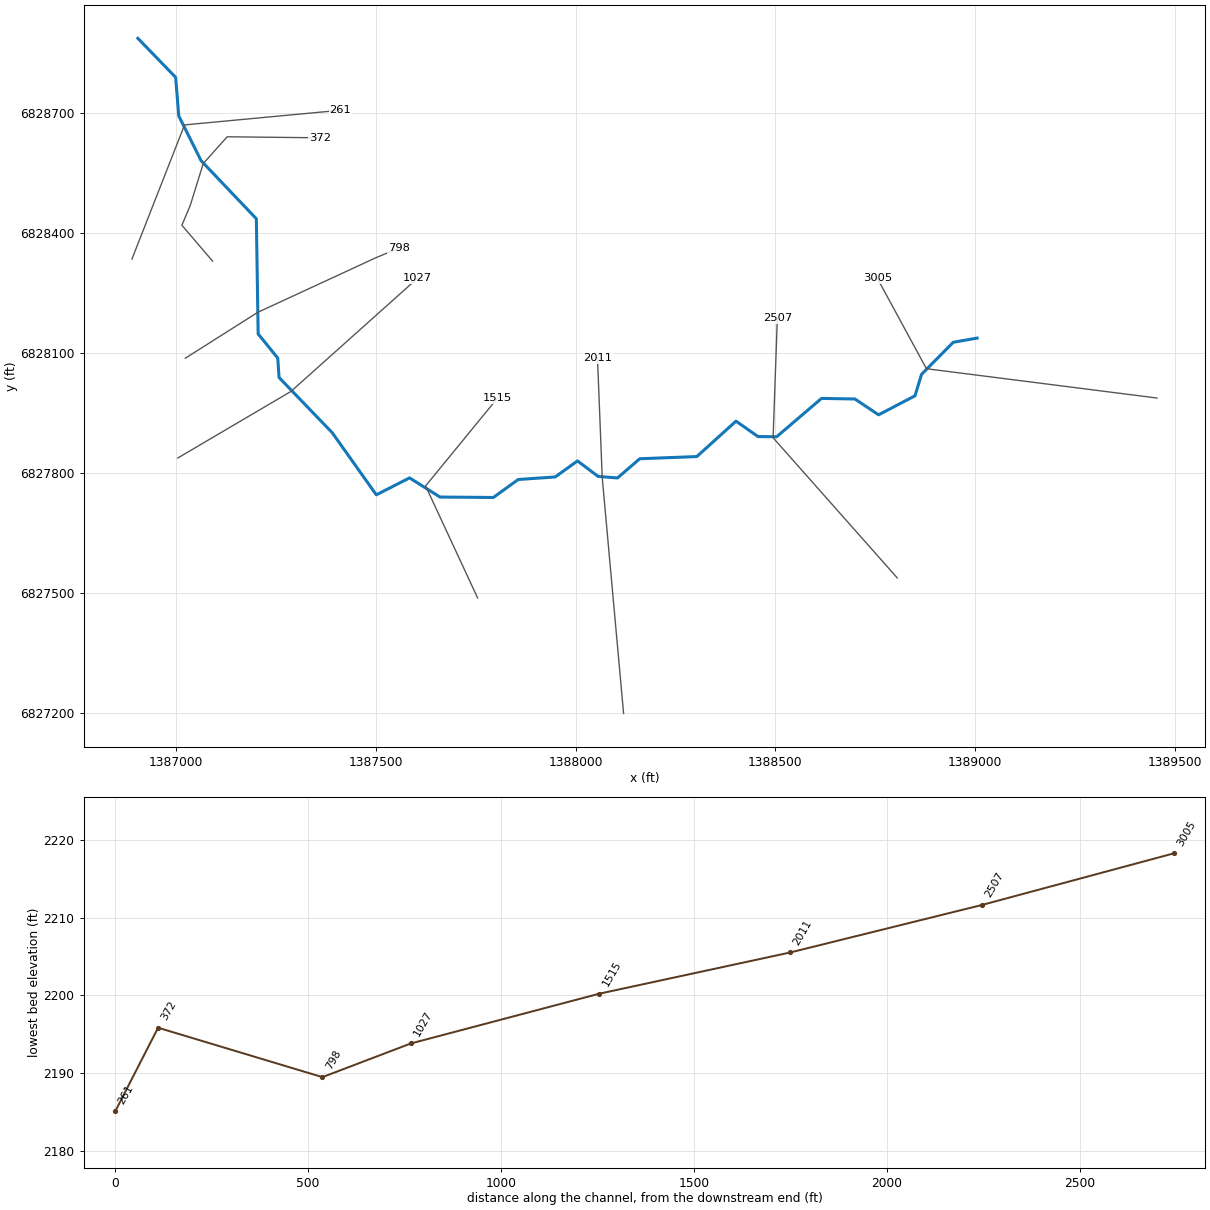
--- Sweetwater Creek Trib 20T1.prj (project) ---

Proj Title=Sweetwater Creek Trib 20T1 Base Level Engineering
Current Plan=p01
Default Exp/Contr=0.3,0.1
English Units
Geom File=g01
Flow File=f01
Plan File=p01
Y Axis Title=Elevation
X Axis Title(PF)=Main Channel Distance
X Axis Title(XS)=Station
BEGIN DESCRIPTION:
Sweetwater Creek Trib 20T1
END DESCRIPTION:
DSS Export Rating Curves= 0
DSS Export Rating Curve Sorted= 0
DSS Export Volume Flow Curves= 0
DXF OffsetX= 0
DXF OffsetY= 0
DXF ScaleX= 1
DXF ScaleY= 10

--- Sweetwater Creek Trib 20T1.p01 (plan) ---

Plan Title=Multiple Run
Short Identifier=Multiple
Geom File=g01
Flow File=f01
Subcritical Flow
K Sum by GR= 0
Std Step Tol= 0.01
Critical Tol= 0.01
Num of Std Step Trials= 20
Max Error Tol= 0.3
Flow Tol Ratio= 0.001
Split Flow NTrial= 30
Split Flow Tol= 0.02
Split Flow Ratio= 0.02
Log Output Level= 0
Friction Slope Method= 1
Unsteady Friction Slope Method= 2
Unsteady Bridges Friction Slope Method= 1
Parabolic Critical Depth
Global Vel Dist=  1 , 1 , 1
Global Log Level= 0
CheckData=True
Encroach Param= -1, 0, 0, 0
BEGIN DESCRIPTION:
Multiple Run
END DESCRIPTION:

--- Sweetwater Creek Trib 20T1.f01 (steady flow) ---

Flow Title=Multiple
Number of Profiles=7
Profile Names=10-year,25-year,50-year,1pct_min,100-year,1pct_plu,500-year
River Rch & RM= Sweetwater Creek,Reach-1,3005
      64      83      98      57     114     228     159
River Rch & RM= Sweetwater Creek,Reach-1,2011
     226     320     401     250     498     994     780
River Rch & RM= Sweetwater Creek,Reach-1,798
     418     617     790     504    1006    2008    1652
Boundary for River Rch & Prof#=Sweetwater Creek,Reach-1,1
Up Type=0
Dn Type=3
Dn Slope=0.005
Boundary for River Rch & Prof#=Sweetwater Creek,Reach-1,2
Up Type=0
Dn Type=3
Dn Slope=0.005
Boundary for River Rch & Prof#=Sweetwater Creek,Reach-1,3
Up Type=0
Dn Type=3
Dn Slope=0.005
Boundary for River Rch & Prof#=Sweetwater Creek,Reach-1,4
Up Type=0
Dn Type=3
Dn Slope=0.005
Boundary for River Rch & Prof#=Sweetwater Creek,Reach-1,5
Up Type=0
Dn Type=3
Dn Slope=0.005
Boundary for River Rch & Prof#=Sweetwater Creek,Reach-1,6
Up Type=0
Dn Type=3
Dn Slope=0.005
Boundary for River Rch & Prof#=Sweetwater Creek,Reach-1,7
Up Type=0
Dn Type=3
Dn Slope=0.005

--- Sweetwater Creek Trib 20T1.g01 (geometry) ---

Geom Title=Existing Conditions

River Reach=Sweetwater Creek,Reach-1
Reach XY= 30
      1389005.00      6828138.00      1388945.18      6828127.49
      1388865.87      6828047.43      1388849.38      6827993.56
      1388758.35      6827946.03      1388699.11      6827985.64
      1388615.49      6827987.05      1388503.35      6827891.17
      1388456.65      6827891.59      1388401.60      6827930.16
      1388303.53      6827841.56      1388160.79      6827836.09
      1388105.00      6827788.00      1388056.36      6827792.00
      1388005.04      6827830.69      1387949.11      6827790.54
      1387856.60      6827784.15      1387794.49      6827739.20
      1387660.93      6827740.28      1387584.79      6827788.21
      1387501.58      6827745.81      1387391.37      6827901.21
      1387258.27      6828039.36      1387255.00      6828088.00
      1387205.96      6828148.40      1387201.46      6828436.54
      1387063.14      6828581.94      1387007.33      6828693.97
      1386999.54      6828790.45      1386905.00      6828888.00

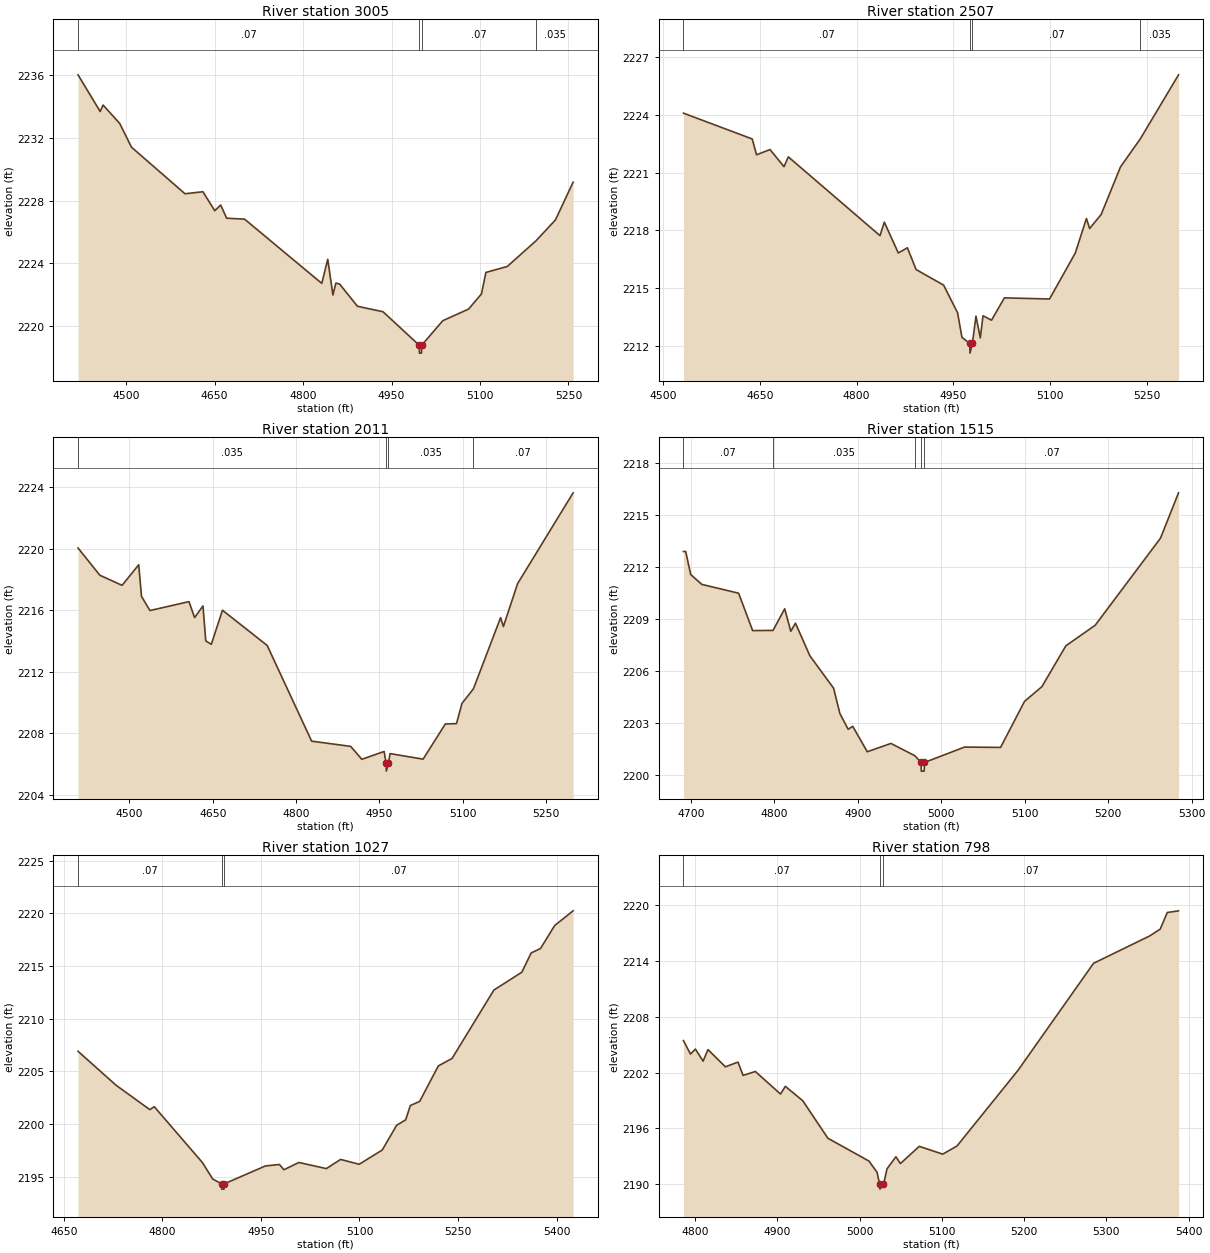
Type RM Length L Ch R = 1,3005,498,498,498
BEGIN DESCRIPTION:
Sweetwater Creek Trib 20T1 5.0
END DESCRIPTION:
XS GIS Cut Line= 3
      1389454.99      6827988.00      1388878.04      6828061.37
      1388754.99      6828288.02
#Sta/Elev= 30
  4418.4 2236.04  4455.9 2233.70  4460.9 2234.11  4489.0 2232.94  4509.1 2231.42
  4599.8 2228.45  4630.1 2228.58  4650.2 2227.37  4660.3 2227.73  4670.4 2226.89
  4700.8 2226.83  4831.7 2222.73  4841.8 2224.27  4850.6 2221.99  4855.6 2222.75
  4861.9 2222.69  4892.2 2221.27  4935.6 2220.92  4997.0 2218.78  4997.3 2218.28
  5000.8 2218.28  5001.0 2218.78  5036.9 2220.35  5080.6 2221.09  5102.5 2222.06
  5110.0 2223.43  5146.2 2223.81  5195.0 2225.45  5227.9 2226.78  5257.9 2229.19
#Mann=4,-1,0
  4418.4    0.07       0  4997.0    0.07       0  5001.0    0.07       0
  5195.0   0.035       0
Bank Sta=4997,5001
Exp/Cntr=0.3,0.1

Type RM Length L Ch R = 1,2507,496,496,496
BEGIN DESCRIPTION:
Sweetwater Creek Trib 20T1 4.0
END DESCRIPTION:
XS GIS Cut Line= 3
      1388805.02      6827537.97      1388494.36      6827888.65
      1388505.00      6828187.97
#Sta/Elev= 30
  4531.5 2224.09  4638.2 2222.75  4644.9 2221.93  4665.8 2222.20  4687.5 2221.31
  4694.2 2221.82  4836.4 2217.73  4843.1 2218.43  4864.8 2216.83  4878.9 2217.10
  4892.4 2215.97  4935.1 2215.16  4956.8 2213.72  4963.5 2212.45  4975.7 2212.13
  4976.0 2211.63  4979.7 2212.13  4985.3 2213.55  4992.0 2212.42  4996.2 2213.57
  5009.4 2213.34  5029.4 2214.50  5099.4 2214.44  5139.4 2216.83  5156.6 2218.62
  5161.6 2218.10  5179.5 2218.83  5209.5 2221.30  5240.3 2222.76  5299.5 2226.08
#Mann=4,-1,0
  4531.5    0.07       0  4975.7    0.07       0  4979.7    0.07       0
  5240.3   0.035       0
Bank Sta=4975.7,4979.7
Exp/Cntr=0.3,0.1

Type RM Length L Ch R = 1,2011,496,496,496
BEGIN DESCRIPTION:
Sweetwater Creek Trib 20T1 3.0
END DESCRIPTION:
XS GIS Cut Line= 3
      1388120.30      6827199.00      1388066.85      6827789.09
      1388055.00      6828087.95
#Sta/Elev= 30
  4407.5 2220.05  4446.7 2218.28  4486.8 2217.62  4516.8 2218.96  4521.8 2216.90
  4537.0 2215.98  4607.3 2216.56  4617.4 2215.52  4632.5 2216.28  4637.5 2214.01
  4647.5 2213.78  4667.6 2216.00  4748.1 2213.71  4828.2 2207.48  4898.5 2207.14
  4918.6 2206.30  4958.7 2206.81  4962.4 2206.03  4962.7 2205.53  4966.4 2206.03
  4969.4 2206.67  5028.9 2206.31  5069.0 2208.60  5089.0 2208.62  5099.0 2209.94
  5119.6 2210.89  5168.5 2215.52  5173.5 2214.94  5199.1 2217.73  5299.1 2223.64
#Mann=4,-1,0
  4407.5   0.035       0  4962.4   0.035       0  4966.4   0.035       0
  5119.6    0.07       0
Bank Sta=4962.4,4966.4
Exp/Cntr=0.3,0.1

Type RM Length L Ch R = 1,1515,488,488,488
BEGIN DESCRIPTION:
Sweetwater Creek Trib 20T1 2.0
END DESCRIPTION:
XS GIS Cut Line= 3
      1387754.99      6827488.02      1387624.88      6827768.07
      1387805.02      6827988.02
#Sta/Elev= 30
  4691.2 2212.90  4693.9 2212.90  4699.9 2211.57  4713.2 2211.00  4757.3 2210.49
  4774.1 2208.33  4798.5 2208.34  4812.5 2209.59  4819.8 2208.29  4825.4 2208.76
  4842.7 2206.87  4871.1 2205.00  4878.6 2203.54  4888.5 2202.63  4894.0 2202.80
  4911.4 2201.33  4939.8 2201.81  4968.4 2201.10  4975.9 2200.71  4976.1 2200.21
  4979.6 2200.21  4979.9 2200.71  5028.0 2201.60  5071.1 2201.58  5099.8 2204.24
  5120.6 2205.09  5149.3 2207.45  5184.5 2208.64  5262.7 2213.67  5284.3 2216.29
#Mann=5,-1,0
  4691.2    0.07       0  4798.5   0.035       0  4968.4    0.07       0
  4975.9    0.07       0  4979.9    0.07       0
Bank Sta=4975.9,4979.9
Exp/Cntr=0.3,0.1

Type RM Length L Ch R = 1,1027,229,229,229
BEGIN DESCRIPTION:
Sweetwater Creek Trib 20T1 1.0
END DESCRIPTION:
XS GIS Cut Line= 3
      1387005.00      6827838.00      1387288.04      6828004.54
      1387604.98      6828287.99
#Sta/Elev= 30
  4671.6 2206.90  4729.6 2203.67  4780.9 2201.36  4787.6 2201.64  4861.0 2196.33
  4876.6 2194.77  4890.1 2194.31  4890.3 2193.81  4893.8 2193.81  4894.1 2194.31
  4956.7 2196.01  4978.2 2196.15  4984.9 2195.65  5007.7 2196.34  5049.6 2195.76
  5071.2 2196.63  5099.6 2196.17  5134.7 2197.53  5156.5 2199.87  5170.3 2200.39
  5177.4 2201.75  5191.6 2202.14  5220.0 2205.51  5240.9 2206.22  5304.5 2212.71
  5347.1 2214.41  5361.3 2216.24  5375.5 2216.66  5397.2 2218.85  5425.2 2220.24
#Mann=3,-1,0
  4671.6    0.07       0  4890.1    0.07       0  4894.1    0.07       0
Bank Sta=4890.1,4894.1
Exp/Cntr=0.3,0.1

Type RM Length L Ch R = 1,798,426,426,426
BEGIN DESCRIPTION:
Sweetwater Creek Trib 20T1 4380
END DESCRIPTION:
XS GIS Cut Line= 4
      1387023.78      6828087.70      1387204.75      6828202.29
      1387499.47      6828338.57      1387557.60      6828362.86
#Sta/Elev= 30
  4785.8 2205.45  4794.4 2204.00  4800.3 2204.54  4809.7 2203.24  4815.6 2204.48
  4836.8 2202.63  4852.1 2203.14  4858.3 2201.70  4873.2 2202.13  4903.8 2199.70
  4909.7 2200.53  4930.9 2198.98  4961.4 2194.95  5011.3 2192.50  5021.2 2191.29
  5024.4 2189.98  5024.7 2189.48  5029.0 2189.98  5033.3 2191.66  5044.1 2192.96
  5049.6 2192.23  5072.5 2194.08  5101.0 2193.24  5118.4 2194.12  5192.7 2202.27
  5284.4 2213.76  5352.4 2216.69  5365.4 2217.43  5374.0 2219.22  5387.7 2219.40
#Mann=3,-1,0
  4785.8    0.07       0  5024.4    0.07       0  5029.0    0.07       0
Bank Sta=5024.4,5029
Exp/Cntr=0.3,0.1

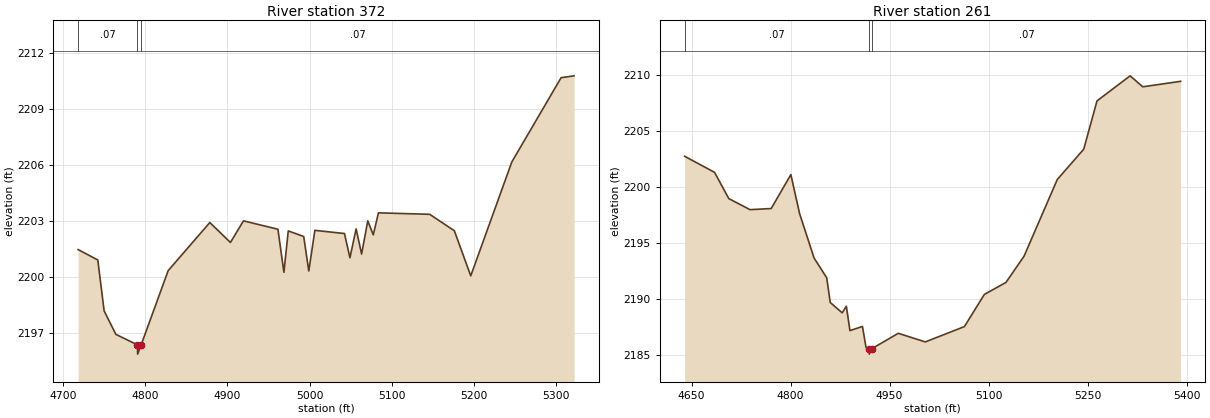
Type RM Length L Ch R = 1,372,111,111,111
BEGIN DESCRIPTION:
Sweetwater Creek Trib 20T1 2790
END DESCRIPTION:
XS GIS Cut Line= 6
      1387091.99      6828330.50      1387015.18      6828420.34
      1387036.01      6828469.82      1387068.62      6828574.79
      1387128.46      6828641.69      1387360.78      6828639.09
#Sta/Elev= 30
  4718.2 2201.45  4742.2 2200.89  4749.9 2198.16  4764.2 2196.90  4790.4 2196.34
  4790.7 2195.84  4795.0 2196.34  4827.9 2200.32  4878.6 2202.90  4903.7 2201.83
  4919.6 2202.99  4961.5 2202.54  4968.8 2200.23  4974.1 2202.45  4992.9 2202.15
  4999.1 2200.30  5006.5 2202.48  5042.5 2202.31  5049.2 2201.01  5056.7 2202.56
  5063.4 2201.21  5070.9 2202.99  5077.6 2202.24  5083.9 2203.42  5146.3 2203.34
  5176.3 2202.46  5196.3 2200.04  5246.3 2206.15  5306.3 2210.67  5322.1 2210.77
#Mann=3,-1,0
  4718.2    0.07       0  4790.4    0.07       0  4795.0    0.07       0
Bank Sta=4790.4,4795
Exp/Cntr=0.3,0.1

Type RM Length L Ch R = 1,261,0,0,0
BEGIN DESCRIPTION:
Sweetwater Creek Trib 20T1 4379
END DESCRIPTION:
XS GIS Cut Line= 3
      1386890.17      6828335.70      1387021.83      6828671.40
      1387411.12      6828707.98
#Sta/Elev= 30
  4639.4 2202.76  4684.8 2201.32  4706.3 2198.98  4738.5 2197.99  4770.6 2198.09
  4800.4 2201.12  4813.7 2197.62  4835.6 2193.67  4854.7 2191.91  4860.1 2189.70
  4878.2 2188.78  4884.5 2189.37  4889.9 2187.19  4908.9 2187.56  4914.3 2185.69
  4918.9 2185.59  4919.2 2185.09  4923.5 2185.59  4963.2 2186.95  5004.1 2186.18
  5063.4 2187.55  5093.6 2190.42  5126.3 2191.49  5153.8 2193.84  5204.1 2200.68
  5244.2 2203.39  5264.3 2207.70  5314.5 2209.94  5333.7 2208.96  5391.0 2209.45
#Mann=3,-1,0
  4639.4    0.07       0  4918.9    0.07       0  4923.5    0.07       0
Bank Sta=4918.9,4923.5
Exp/Cntr=0.3,0.1

Chan Stop Cuts=-1