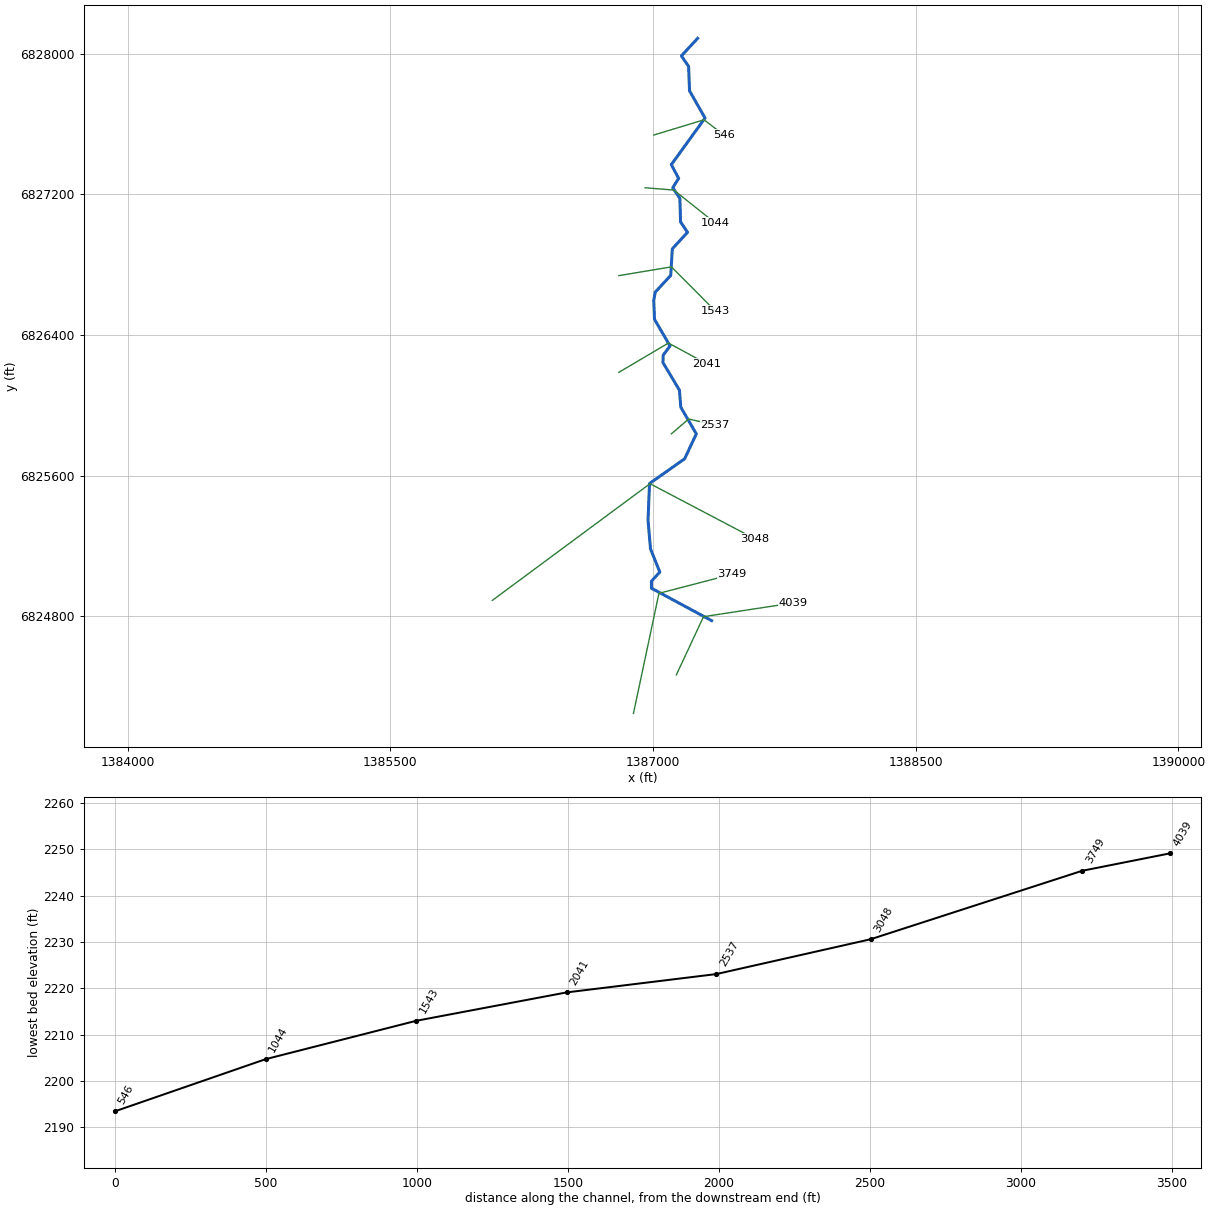
--- Sweetwater Creek Trib 20T1_2.prj (project) ---

Proj Title=Sweetwater Creek Trib 20T1_2 Base Level Engineering
Current Plan=p01
Default Exp/Contr=0.3,0.1
English Units
Geom File=g01
Flow File=f01
Plan File=p01
Y Axis Title=Elevation
X Axis Title(PF)=Main Channel Distance
X Axis Title(XS)=Station
BEGIN DESCRIPTION:
Sweetwater Creek Trib 20T1_2
END DESCRIPTION:
DSS Export Rating Curves= 0
DSS Export Rating Curve Sorted= 0
DSS Export Volume Flow Curves= 0
DXF OffsetX= 0
DXF OffsetY= 0
DXF ScaleX= 1
DXF ScaleY= 10

--- Sweetwater Creek Trib 20T1_2.p01 (plan) ---

Plan Title=Multiple Run
Short Identifier=Multiple
Geom File=g01
Flow File=f01
Subcritical Flow
K Sum by GR= 0
Std Step Tol= 0.01
Critical Tol= 0.01
Num of Std Step Trials= 20
Max Error Tol= 0.3
Flow Tol Ratio= 0.001
Split Flow NTrial= 30
Split Flow Tol= 0.02
Split Flow Ratio= 0.02
Log Output Level= 0
Friction Slope Method= 1
Unsteady Friction Slope Method= 2
Unsteady Bridges Friction Slope Method= 1
Parabolic Critical Depth
Global Vel Dist=  1 , 1 , 1
Global Log Level= 0
CheckData=True
Encroach Param= -1, 0, 0, 0
BEGIN DESCRIPTION:
Multiple Run
END DESCRIPTION:

--- Sweetwater Creek Trib 20T1_2.f01 (steady flow) ---

Flow Title=Multiple
Number of Profiles=7
Profile Names=10-year,25-year,50-year,1pct_min,100-year,1pct_plu,500-year
River Rch & RM= Sweetwater Creek,Reach-1,4039
     257     368     463     290     579    1154     916
Boundary for River Rch & Prof#=Sweetwater Creek,Reach-1,1
Up Type=0
Dn Type=3
Dn Slope=0.005
Boundary for River Rch & Prof#=Sweetwater Creek,Reach-1,2
Up Type=0
Dn Type=3
Dn Slope=0.005
Boundary for River Rch & Prof#=Sweetwater Creek,Reach-1,3
Up Type=0
Dn Type=3
Dn Slope=0.005
Boundary for River Rch & Prof#=Sweetwater Creek,Reach-1,4
Up Type=0
Dn Type=3
Dn Slope=0.005
Boundary for River Rch & Prof#=Sweetwater Creek,Reach-1,5
Up Type=0
Dn Type=3
Dn Slope=0.005
Boundary for River Rch & Prof#=Sweetwater Creek,Reach-1,6
Up Type=0
Dn Type=3
Dn Slope=0.005
Boundary for River Rch & Prof#=Sweetwater Creek,Reach-1,7
Up Type=0
Dn Type=3
Dn Slope=0.005

--- Sweetwater Creek Trib 20T1_2.g01 (geometry) ---

Geom Title=Existing Conditions

River Reach=Sweetwater Creek,Reach-1
Reach XY= 30
      1387334.62      6824775.59      1386991.35      6824959.75
      1386991.35      6824999.89      1387039.09      6825051.98
      1386985.92      6825183.27      1386971.81      6825346.03
      1386980.28      6825555.45      1387180.80      6825696.07
      1387247.44      6825838.00      1387158.83      6825989.58
      1387151.17      6826086.42      1387056.95      6826243.72
      1387058.60      6826286.36      1387097.44      6826338.00
      1387008.74      6826489.56      1387004.45      6826597.28
      1387012.82      6826644.18      1387101.44      6826739.47
      1387110.50      6826890.45      1387197.19      6826984.59
      1387157.48      6827043.86      1387153.61      6827177.56
      1387112.79      6827238.10      1387146.68      6827291.23
      1387104.77      6827369.59      1387297.22      6827634.60
      1387208.76      6827789.56      1387203.44      6827928.41
      1387162.22      6827988.11      1387255.00      6828088.00

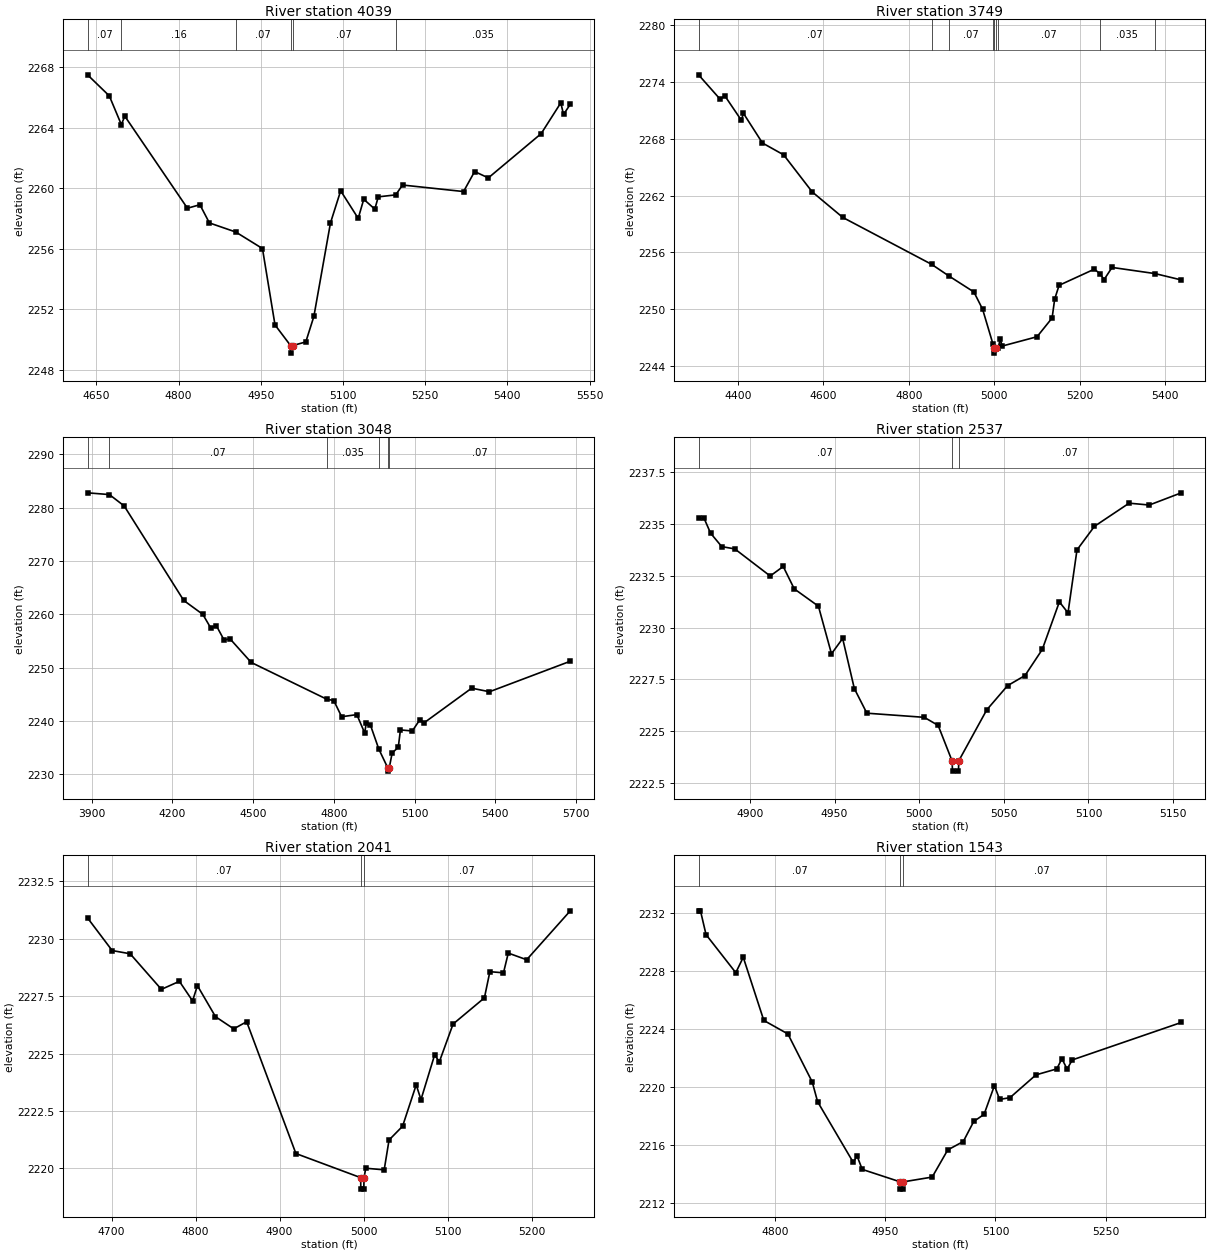
Type RM Length L Ch R = 1,4039,290,290,290
BEGIN DESCRIPTION:
Sweetwater Creek Trib 20T1_2 4166
END DESCRIPTION:
XS GIS Cut Line= 3
      1387133.36      6824466.65      1387288.65      6824798.07
      1387797.49      6824875.55
#Sta/Elev= 30
  4634.0 2267.48  4673.7 2266.09  4695.6 2264.20  4702.0 2264.75  4816.2 2258.68
  4839.0 2258.91  4856.3 2257.71  4904.4 2257.11  4953.1 2256.02  4976.0 2250.98
  5004.4 2249.62  5004.7 2249.12  5008.4 2249.62  5032.2 2249.86  5046.9 2251.54
  5077.2 2257.71  5095.8 2259.83  5127.8 2258.01  5137.9 2259.27  5158.1 2258.62
  5164.4 2259.43  5196.2 2259.56  5208.7 2260.21  5320.0 2259.78  5340.2 2261.10
  5365.2 2260.68  5461.6 2263.60  5497.4 2265.63  5502.4 2264.87  5514.7 2265.53
#Mann=6,-1,0
  4634.0    0.07       0  4695.6    0.16       0  4904.4    0.07       0
  5004.4    0.07       0  5008.4    0.07       0  5196.2   0.035       0
Bank Sta=5004.4,5008.4
Exp/Cntr=0.3,0.1

Type RM Length L Ch R = 1,3749,701,701,701
BEGIN DESCRIPTION:
Sweetwater Creek Trib 20T1_2 6.0
END DESCRIPTION:
XS GIS Cut Line= 3
      1386888.58      6824247.90      1387034.14      6824930.74
      1387451.83      6825039.12
#Sta/Elev= 30
  4308.0 2274.76  4358.4 2272.19  4369.5 2272.54  4408.0 2269.97  4413.1 2270.69
  4457.5 2267.56  4507.1 2266.31  4573.9 2262.40  4645.5 2259.70  4853.3 2254.75
  4894.1 2253.51  4952.3 2251.83  4972.7 2250.01  4996.9 2246.34  5000.2 2245.87
  5000.5 2245.37  5004.2 2245.87  5009.2 2245.87  5013.7 2246.84  5018.9 2246.12
  5100.1 2247.10  5135.4 2249.08  5141.4 2251.07  5151.7 2252.53  5234.4 2254.24
  5247.1 2253.76  5257.1 2253.14  5275.7 2254.42  5376.2 2253.77  5437.7 2253.10
#Mann=9,-1,0
  4308.0    0.07       0  4853.3    0.16       0  4894.1    0.07       0
  4996.9   0.035       0  5000.2   0.035       0  5004.2   0.035       0
  5009.2    0.07       0  5247.1   0.035       0  5376.2    0.07       0
Bank Sta=5000.2,5004.2
Exp/Cntr=0.3,0.1

Type RM Length L Ch R = 1,3048,511,511,511
BEGIN DESCRIPTION:
Sweetwater Creek Trib 20T1_2 5.0
END DESCRIPTION:
XS GIS Cut Line= 3
      1386082.63      6824890.62      1386983.10      6825554.45
      1387581.28      6825241.30
#Sta/Elev= 30
  3884.8 2282.78  3966.0 2282.45  4020.9 2280.32  4242.3 2262.59  4313.2 2259.98
  4342.5 2257.44  4363.4 2257.86  4392.6 2255.13  4413.5 2255.44  4492.9 2250.97
  4772.9 2244.09  4799.9 2243.81  4829.1 2240.78  4885.5 2241.18  4914.7 2237.74
  4921.0 2239.69  4935.6 2239.28  4967.4 2234.69  5001.5 2231.08  5001.8 2230.58
  5005.5 2231.08  5016.9 2234.00  5039.5 2235.04  5047.5 2238.31  5091.6 2238.11
  5119.3 2240.19  5135.7 2239.65  5312.3 2246.14  5378.5 2245.47  5678.7 2251.19
#Mann=6,-1,0
  3884.8   0.035       0  3966.0    0.07       0  4772.9   0.035       0
  4967.4    0.07       0  5001.5    0.07       0  5005.5    0.07       0
Bank Sta=5001.5,5005.5
Exp/Cntr=0.3,0.1

Type RM Length L Ch R = 1,2537,496,496,496
BEGIN DESCRIPTION:
Sweetwater Creek Trib 20T1_2 4.0
END DESCRIPTION:
XS GIS Cut Line= 3
      1387105.00      6825838.00      1387204.11      6825922.58
      1387355.00      6825888.00
#Sta/Elev= 30
  4869.7 2235.27  4873.0 2235.27  4876.8 2234.56  4883.4 2233.91  4891.1 2233.80
  4912.0 2232.49  4919.7 2232.95  4926.2 2231.87  4940.5 2231.03  4948.2 2228.73
  4954.8 2229.47  4961.7 2227.05  4969.1 2225.86  5003.0 2225.66  5011.2 2225.27
  5019.4 2223.56  5019.7 2223.06  5023.2 2223.06  5023.4 2223.56  5039.9 2226.02
  5052.2 2227.19  5062.5 2227.68  5072.7 2228.94  5082.8 2231.24  5087.9 2230.71
  5093.2 2233.75  5103.5 2234.89  5124.0 2236.01  5135.9 2235.92  5154.8 2236.51
#Mann=3,-1,0
  4869.7    0.07       0  5019.4    0.07       0  5023.4    0.07       0
Bank Sta=5019.4,5023.4
Exp/Cntr=0.3,0.1

Type RM Length L Ch R = 1,2041,498,498,498
BEGIN DESCRIPTION:
Sweetwater Creek Trib 20T1_2 3.0
END DESCRIPTION:
XS GIS Cut Line= 3
      1386805.04      6826188.02      1387088.32      6826354.55
      1387304.97      6826238.02
#Sta/Elev= 30
  4671.4 2230.91  4700.7 2229.49  4722.1 2229.35  4759.3 2227.80  4780.7 2228.15
  4796.4 2227.30  4802.2 2227.96  4823.7 2226.61  4845.4 2226.08  4860.8 2226.39
  4919.4 2220.65  4996.5 2219.60  4996.7 2219.10  5000.2 2219.10  5000.5 2219.60
  5002.6 2220.01  5024.5 2219.94  5030.3 2221.24  5046.4 2221.84  5062.6 2223.64
  5068.3 2223.00  5084.5 2224.94  5090.2 2224.65  5106.5 2226.29  5143.8 2227.43
  5150.3 2228.57  5166.5 2228.52  5172.2 2229.38  5194.1 2229.09  5246.0 2231.22
#Mann=3,-1,0
  4671.4    0.07       0  4996.5    0.07       0  5000.5    0.07       0
Bank Sta=4996.5,5000.5
Exp/Cntr=0.3,0.1

Type RM Length L Ch R = 1,1543,499,499,499
BEGIN DESCRIPTION:
Sweetwater Creek Trib 20T1_2 2.0
END DESCRIPTION:
XS GIS Cut Line= 3
      1386804.97      6826737.99      1387105.36      6826787.85
      1387355.00      6826538.00
#Sta/Elev= 30
  4695.5 2232.14  4698.1 2232.14  4705.7 2230.50  4746.2 2227.88  4756.4 2228.94
  4784.4 2224.59  4817.2 2223.66  4850.4 2220.35  4857.7 2218.99  4906.3 2214.81
  4911.4 2215.26  4918.5 2214.33  4970.3 2213.47  4970.6 2212.97  4974.1 2212.97
  4974.3 2213.47  5013.8 2213.80  5035.0 2215.67  5056.2 2216.25  5070.4 2217.63
  5084.5 2218.12  5098.6 2220.10  5105.7 2219.15  5119.8 2219.27  5155.2 2220.84
  5183.5 2221.25  5190.6 2221.95  5197.6 2221.24  5204.7 2221.87  5353.2 2224.45
#Mann=3,-1,0
  4695.5    0.07       0  4970.3    0.07       0  4974.3    0.07       0
Bank Sta=4970.3,4974.3
Exp/Cntr=0.3,0.1

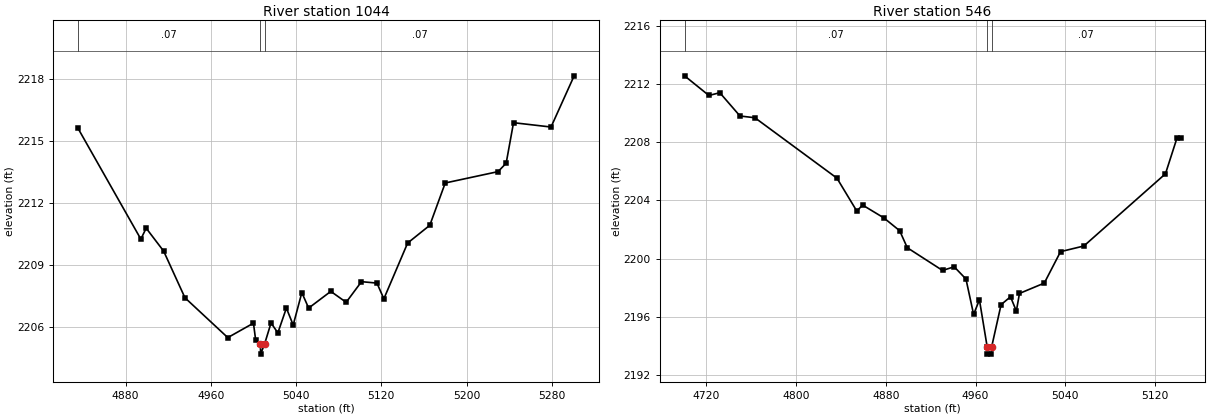
Type RM Length L Ch R = 1,1044,498,498,498
BEGIN DESCRIPTION:
Sweetwater Creek Trib 20T1_2 1.0
END DESCRIPTION:
XS GIS Cut Line= 3
      1386954.99      6827238.00      1387119.07      6827224.84
      1387355.04      6827037.97
#Sta/Elev= 30
  4835.4 2215.61  4894.3 2210.25  4899.3 2210.78  4915.7 2209.67  4935.7 2207.41
  4975.9 2205.48  5000.0 2206.18  5002.1 2205.35  5006.5 2205.18  5006.7 2204.68
  5010.5 2205.18  5016.5 2206.19  5022.9 2205.71  5030.9 2206.91  5037.3 2206.09
  5045.4 2207.66  5051.8 2206.91  5072.6 2207.72  5087.0 2207.19  5101.4 2208.19
  5115.9 2208.12  5122.4 2207.36  5144.7 2210.06  5165.5 2210.92  5180.0 2212.97
  5229.6 2213.52  5237.2 2213.93  5244.1 2215.89  5279.3 2215.68  5301.0 2218.16
#Mann=3,-1,0
  4835.4    0.07       0  5006.5    0.07       0  5010.5    0.07       0
Bank Sta=5006.5,5010.5
Exp/Cntr=0.3,0.1

Type RM Length L Ch R = 1,546,0,0,0
BEGIN DESCRIPTION:
Sweetwater Creek Trib 20T1_2 2878
END DESCRIPTION:
XS GIS Cut Line= 3
      1387004.97      6827537.99      1387291.46      6827624.63
      1387404.99      6827538.01
#Sta/Elev= 30
  4700.7 2212.56  4722.4 2211.21  4732.1 2211.40  4750.1 2209.80  4763.4 2209.68
  4836.5 2205.53  4854.2 2203.27  4859.4 2203.68  4878.3 2202.80  4892.4 2201.92
  4899.2 2200.75  4930.6 2199.19  4941.0 2199.44  4951.5 2198.60  4958.3 2196.17
  4963.5 2197.17  4970.4 2193.94  4970.6 2193.44  4974.1 2193.44  4974.4 2193.94
  4982.8 2196.84  4991.2 2197.38  4996.4 2196.40  4999.2 2197.61  5021.3 2198.32
  5035.8 2200.48  5056.6 2200.87  5129.3 2205.83  5139.7 2208.32  5142.8 2208.32
#Mann=3,-1,0
  4700.7    0.07       0  4970.4    0.07       0  4974.4    0.07       0
Bank Sta=4970.4,4974.4
Exp/Cntr=0.3,0.1

Chan Stop Cuts=-1