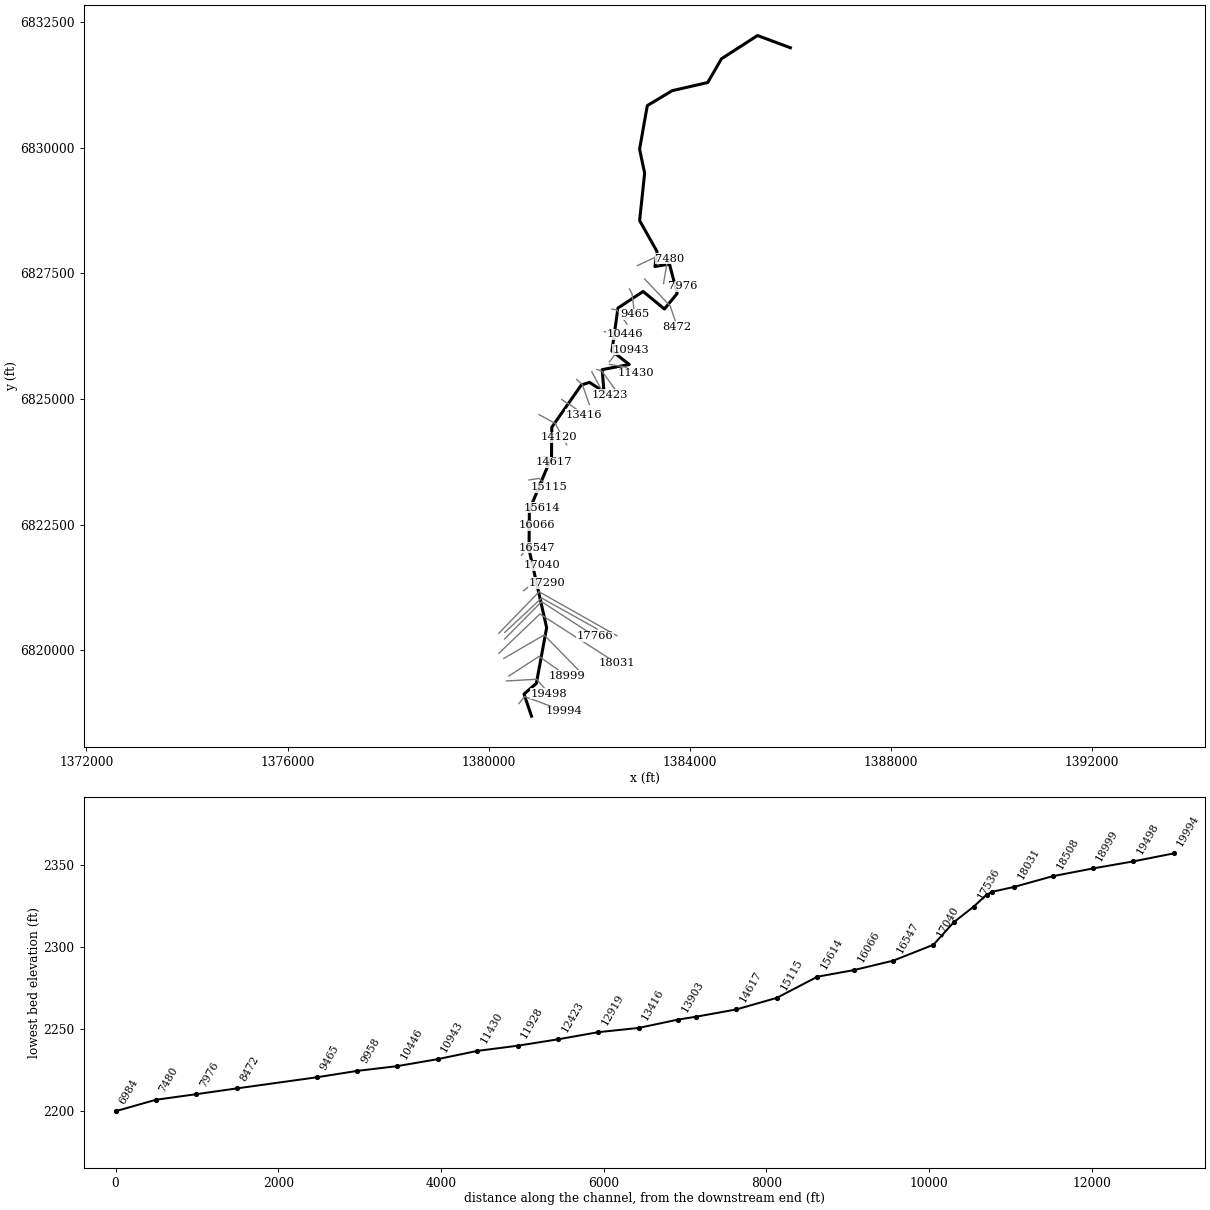
--- Sweetwater Creek Trib 20T2.prj (project) ---

Proj Title=Sweetwater Creek Trib 20T2 Base Level Engineering
Current Plan=p01
Default Exp/Contr=0.3,0.1
English Units
Geom File=g01
Flow File=f01
Plan File=p01
Y Axis Title=Elevation
X Axis Title(PF)=Main Channel Distance
X Axis Title(XS)=Station
BEGIN DESCRIPTION:
Sweetwater Creek Trib 20T2
END DESCRIPTION:
DSS Export Rating Curves= 0
DSS Export Rating Curve Sorted= 0
DSS Export Volume Flow Curves= 0
DXF OffsetX= 0
DXF OffsetY= 0
DXF ScaleX= 1
DXF ScaleY= 10

--- Sweetwater Creek Trib 20T2.p01 (plan) ---

Plan Title=Multiple Run
Short Identifier=Multiple
Geom File=g01
Flow File=f01
Subcritical Flow
K Sum by GR= 0
Std Step Tol= 0.01
Critical Tol= 0.01
Num of Std Step Trials= 20
Max Error Tol= 0.3
Flow Tol Ratio= 0.001
Split Flow NTrial= 30
Split Flow Tol= 0.02
Split Flow Ratio= 0.02
Log Output Level= 0
Friction Slope Method= 1
Unsteady Friction Slope Method= 2
Unsteady Bridges Friction Slope Method= 1
Parabolic Critical Depth
Global Vel Dist=  1 , 1 , 1
Global Log Level= 0
CheckData=True
Encroach Param= -1, 0, 0, 0
BEGIN DESCRIPTION:
Multiple Run
END DESCRIPTION:

--- Sweetwater Creek Trib 20T2.f01 (steady flow) ---

Flow Title=Multiple
Number of Profiles=7
Profile Names=10-year,25-year,50-year,1pct_min,100-year,1pct_plu,500-year
River Rch & RM= Sweetwater Creek,Reach-1,19994
     362     530     676     430     858    1712    1399
River Rch & RM= Sweetwater Creek,Reach-1,18508
     576     864    1121     723    1442    2878    2421
River Rch & RM= Sweetwater Creek,Reach-1,13416
     588     877    1132     726    1449    2892    2407
River Rch & RM= Sweetwater Creek,Reach-1,4992
     668    1003    1300     837    1670    3333    2795
River Rch & RM= Sweetwater Creek,Reach-1,4505
     735    1105    1434     924    1844    3679    3089
Boundary for River Rch & Prof#=Sweetwater Creek,Reach-1,1
Up Type=0
Dn Type=3
Dn Slope=0.005
Boundary for River Rch & Prof#=Sweetwater Creek,Reach-1,2
Up Type=0
Dn Type=3
Dn Slope=0.005
Boundary for River Rch & Prof#=Sweetwater Creek,Reach-1,3
Up Type=0
Dn Type=3
Dn Slope=0.005
Boundary for River Rch & Prof#=Sweetwater Creek,Reach-1,4
Up Type=0
Dn Type=3
Dn Slope=0.005
Boundary for River Rch & Prof#=Sweetwater Creek,Reach-1,5
Up Type=0
Dn Type=3
Dn Slope=0.005
Boundary for River Rch & Prof#=Sweetwater Creek,Reach-1,6
Up Type=0
Dn Type=3
Dn Slope=0.005
Boundary for River Rch & Prof#=Sweetwater Creek,Reach-1,7
Up Type=0
Dn Type=3
Dn Slope=0.005

--- Sweetwater Creek Trib 20T2.g01 (geometry) ---

Geom Title=Existing Conditions
Program Version=4.10

River Reach=Sweetwater Creek,Reach-1
Reach XY= 30
        1380855.        6818688.      1380705.53      6819127.55
      1380951.18      6819339.58      1381155.78      6820448.05
      1380805.52      6822003.22      1380812.32       6822788.1
      1381252.76      6823843.93      1381258.54      6824436.54
      1381845.19      6825277.49      1382008.42      6825330.21
      1382296.68      6825140.96      1382259.99        6825583.
      1382800.06      6825685.43      1382455.42      6825953.64
      1382574.58      6826808.57      1383075.15      6827138.37
      1383498.89      6826789.79      1383753.78       6827098.5
      1383599.42      6827683.24      1383310.35      6827635.23
      1383352.86      6827932.03      1383005.77      6828548.69
      1383105.81      6829493.06      1383005.01        6829968.
      1383158.61      6830836.52      1383656.55      6831134.25
       1384361.5      6831295.73      1384634.52      6831768.37
      1385351.67      6832230.39        1386005.        6831988.

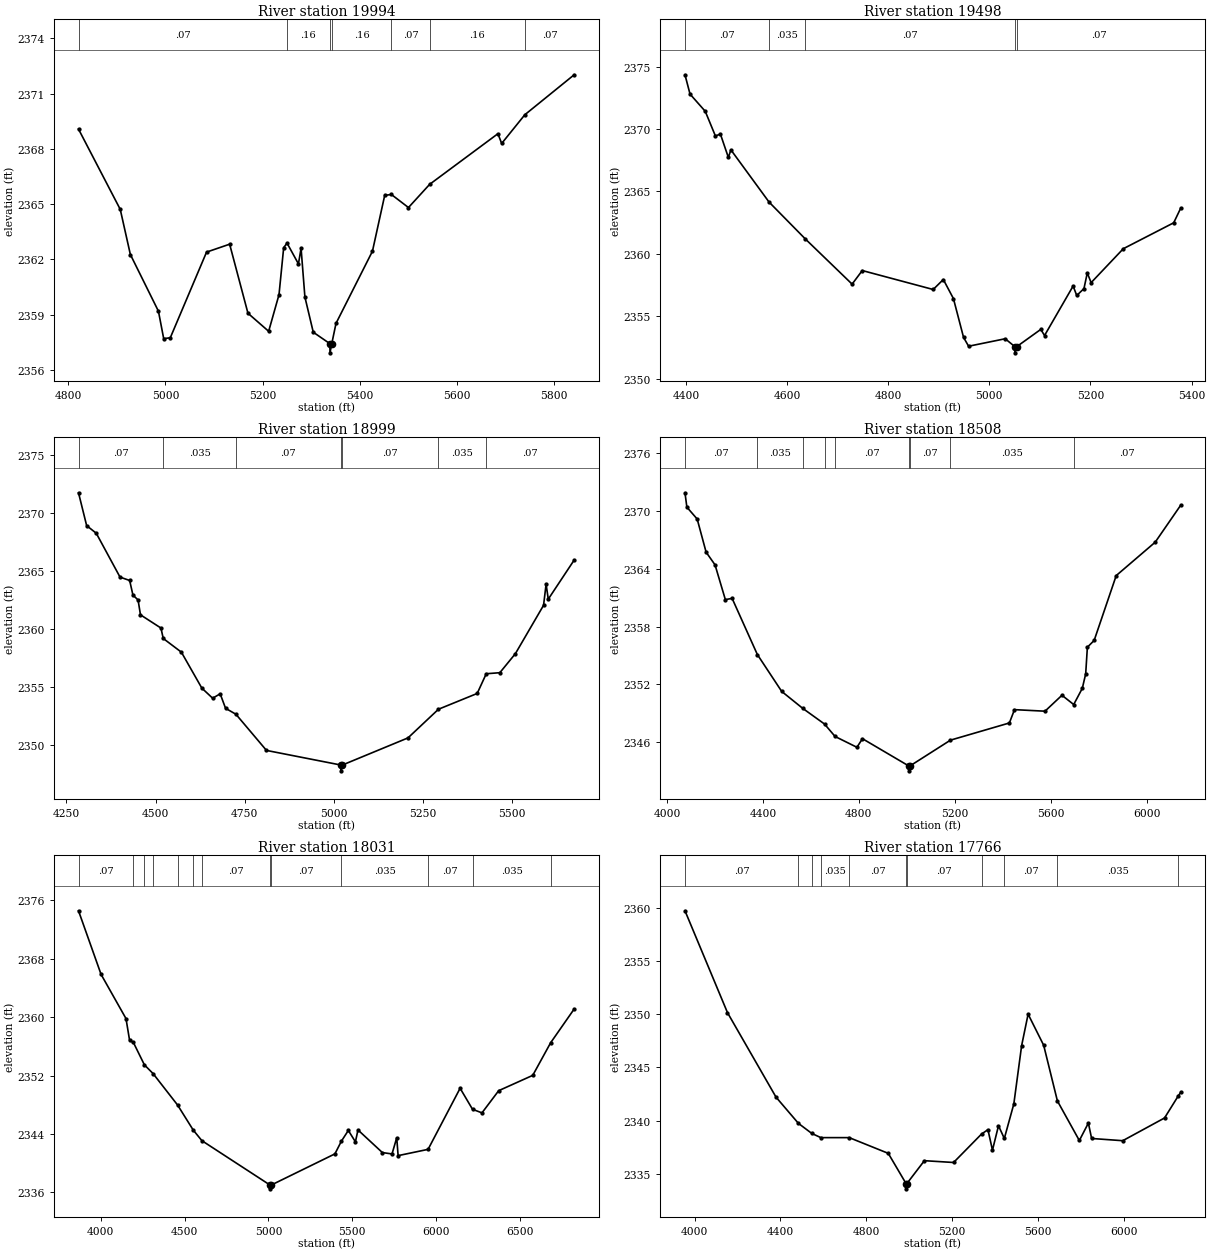
Type RM Length L Ch R = 1 ,19994   ,496,496,496
BEGIN DESCRIPTION:
Sweetwater Creek Trib 20T2 39.0
END DESCRIPTION:
XS GIS Cut Line= 3
      1380604.98      6818937.97      1380715.54      6819078.49
      1381504.99        6818788.
#Sta/Elev= 30
  4821.2 2369.07  4907.1 2364.71  4927.9 2362.26  4985.7 2359.18  4996.5 2357.69
  5010.1 2357.74  5084.7 2362.39  5132.2 2362.82  5169.9 2359.07  5212.5 2358.09
  5233.8 2360.08  5243.4 2362.63  5250.3 2362.88  5273.8 2361.75  5279.2  2362.6
  5287.1 2359.95  5304.3 2358.04  5338.4 2357.42  5338.7 2356.92  5342.4 2357.42
  5351.1 2358.52  5426.1 2362.44  5451.3 2365.47    5465 2365.52  5500.2 2364.81
  5543.8 2366.07  5684.3 2368.82    5692 2368.29  5739.7 2369.85  5841.2 2372.02
#Mann= 7 ,-1 , 0
  4821.2     .07       0  5250.3     .16       0  5338.4     .07       0
  5342.4     .16       0    5465     .07       0  5543.8     .16       0
  5739.7     .07       0
Bank Sta=5338.4,5342.4
XS Rating Curve= 0 ,0
Exp/Cntr=0.3,0.1

Type RM Length L Ch R = 1 ,19498   ,499,499,499
BEGIN DESCRIPTION:
Sweetwater Creek Trib 20T2 38.0
END DESCRIPTION:
XS GIS Cut Line= 3
        1380355.        6819388.       1380955.8      6819422.78
      1381204.99      6819138.02
#Sta/Elev= 30
  4398.2 2374.36  4408.2 2372.81  4438.3 2371.43  4458.3 2369.46  4468.3  2369.6
    4484 2367.73    4489 2368.34  4564.5 2364.15  4636.3 2361.19  4728.7 2357.57
  4748.8 2358.66    4889 2357.14  4909.1 2357.94  4929.1 2356.41  4949.1  2353.3
  4959.1 2352.59  5031.5 2353.19  5050.4 2352.56  5050.7 2352.06  5054.4 2352.56
  5101.8 2353.94  5109.3 2353.45  5165.8 2357.42  5172.9 2356.66  5187.2 2357.21
  5193.8 2358.47  5201.4 2357.69    5265 2360.41  5364.7 2362.49  5378.4 2363.65
#Mann= 5 ,-1 , 0
  4398.2     .07       0  4564.5    .035       0  4636.3     .07       0
  5050.4     .07       0  5054.4     .07       0
Bank Sta=5050.4,5054.4
XS Rating Curve= 0 ,0
Exp/Cntr=0.3,0.1

Type RM Length L Ch R = 1 ,18999   ,491,491,491
BEGIN DESCRIPTION:
Sweetwater Creek Trib 20T2 37.0
END DESCRIPTION:
XS GIS Cut Line= 3
      1380404.96      6819487.98       1381005.4      6819877.83
      1381554.98      6819488.01
#Sta/Elev= 30
  4284.1 2371.71  4306.9 2368.88  4333.9 2368.22  4400.5 2364.44  4427.5 2364.15
  4436.7 2362.89  4451.1 2362.47  4457.8 2361.19  4515.2 2360.05  4521.7 2359.15
  4572.5 2357.97  4629.9 2354.87  4660.2    2354  4681.3 2354.38  4696.4 2353.13
  4725.4 2352.62  4811.1  2349.5  5019.8 2348.24    5020 2347.74  5023.8 2348.24
  5207.9 2350.58  5293.3 2353.05  5401.9 2354.41  5427.3 2356.11  5465.4  2356.2
    5509 2357.84    5588 2362.01  5595.1 2363.83  5601.2 2362.54  5673.8 2365.91
#Mann= 7 ,-1 , 0
  4284.1     .07       0  4521.7    .035       0  4725.4     .07       0
  5019.8     .07       0  5023.8     .07       0  5293.3    .035       0
  5427.3     .07       0
Bank Sta=5019.8,5023.8
XS Rating Curve= 0 ,0
Exp/Cntr=0.3,0.1

Type RM Length L Ch R = 1 ,18508   ,477,477,477
BEGIN DESCRIPTION:
Sweetwater Creek Trib 20T2 36.0
END DESCRIPTION:
XS GIS Cut Line= 3
      1380305.01      6819838.01      1381104.84      6820303.06
      1381905.01      6819487.99
#Sta/Elev= 30
  4074.8 2371.86  4082.7 2370.37  4125.7 2369.14  4162.9 2365.71  4200.2 2364.39
  4243.2 2360.79  4271.4 2360.92  4376.7  2355.1  4478.2 2351.28  4565.6 2349.53
  4656.8  2347.9  4700.9 2346.61    4792 2345.49  4815.1 2346.38  5008.7 2343.55
  5008.9 2343.05  5012.8 2343.55  5182.2 2346.23  5427.9 2348.01  5449.2 2349.39
  5576.5 2349.23  5647.2 2350.88  5696.2 2349.92  5732.1  2351.6  5746.2  2353.1
  5753.2 2355.86  5781.5 2356.56  5873.5 2363.28  6036.1 2366.74  6142.2 2370.56
#Mann= 9 ,-1 , 0
  4074.8     .07       0  4376.7    .035       0  4565.6     .07       0
  4656.8    .035       0  4700.9     .07       0  5008.7     .07       0
  5012.8     .07       0  5182.2    .035       0  5696.2     .07       0
Bank Sta=5008.7,5012.8
XS Rating Curve= 0 ,0
Exp/Cntr=0.3,0.1

Type RM Length L Ch R = 1 ,18031   ,265,265,265
BEGIN DESCRIPTION:
Sweetwater Creek Trib 20T2 35.0
END DESCRIPTION:
XS GIS Cut Line= 3
      1380204.98      6819937.98       1381021.6      6820721.48
      1382555.01        6819738.
#Sta/Elev= 30
  3868.3 2374.59  4002.8 2365.87  4151.2 2359.82  4172.6 2356.85    4195 2356.56
  4260.8 2353.48  4312.7 2352.28  4458.4 2347.98  4551.9 2344.54  4603.4 2343.09
  5010.8 2336.99    5011 2336.49  5014.9 2336.99  5396.1 2341.28  5434.9 2343.03
    5476 2344.49  5518.3 2342.93  5533.5 2344.56  5678.9 2341.46  5736.4 2341.27
  5764.4 2343.49  5772.7 2341.04  5951.2  2341.9  6142.1 2350.27    6216 2347.39
  6272.3  2346.9    6372 2349.94  6574.9 2352.04  6681.6 2356.51  6821.7 2361.13
#Mann= 13 ,-1 , 0
  3868.3     .07       0    4195    .035       0  4260.8     .07       0
  4312.7    .035       0  4458.4     .07       0  4551.9    .035       0
  4603.4     .07       0  5010.8     .07       0  5014.9     .07       0
  5434.9    .035       0  5951.2     .07       0    6216    .035       0
  6681.6     .07       0
Bank Sta=5010.8,5014.9
XS Rating Curve= 0 ,0
Exp/Cntr=0.3,0.1

Type RM Length L Ch R = 1 ,17766   ,73,73,73
BEGIN DESCRIPTION:
Sweetwater Creek Trib 20T2 4140
END DESCRIPTION:
XS GIS Cut Line= 4
      1380319.74      6820222.97      1381055.05      6820965.21
       1381533.6      6820655.46      1382117.94      6820277.25
#Sta/Elev= 30
  3955.2 2359.74  4153.4 2350.15  4379.7  2342.2  4484.2 2339.73  4546.8 2338.78
  4588.7 2338.39    4721 2338.39    4903 2336.91  4985.8 2334.07    4986 2333.57
  4989.9 2334.07  5071.4 2336.22  5207.5 2336.05    5338 2338.73  5367.7 2339.14
  5388.8 2337.21  5416.9 2339.51  5444.1 2338.31  5488.4 2341.56  5524.7 2347.04
    5555 2350.01  5627.6 2347.08  5691.6 2341.84  5793.8 2338.12    5836 2339.76
  5851.1 2338.31  5996.2  2338.1  6191.1 2340.24  6255.8 2342.34  6266.1 2342.64
#Mann= 11 ,-1 , 0
  3955.2     .07       0  4484.2    .035       0  4546.8     .07       0
  4588.7    .035       0    4721     .07       0  4985.8     .07       0
  4989.9     .07       0    5338    .035       0  5444.1     .07       0
  5691.6    .035       0  6255.8     .07       0
Bank Sta=4985.8,4989.9
XS Rating Curve= 0 ,0
Exp/Cntr=0.3,0.1

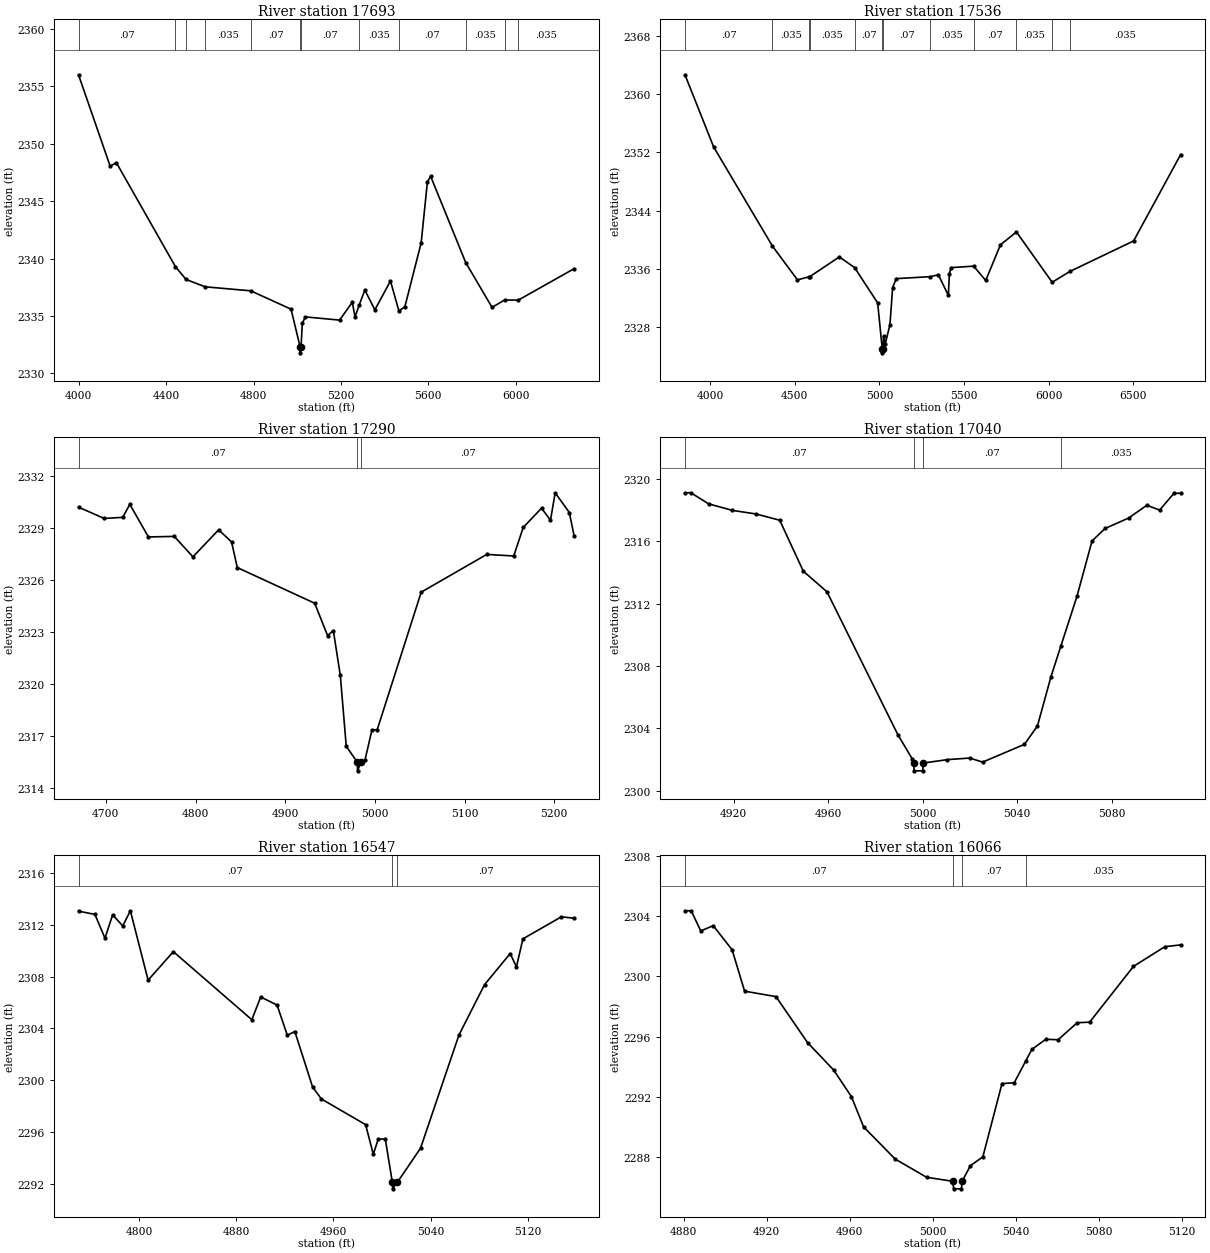
Type RM Length L Ch R = 1 ,17693   ,157,157,157
BEGIN DESCRIPTION:
Sweetwater Creek Trib 20T2 4141
END DESCRIPTION:
XS GIS Cut Line= 3
      1380323.22      6820354.92      1381055.89      6821038.98
      1382161.58      6820421.68
#Sta/Elev= 30
  3998.7    2356  4143.6 2348.04  4171.9 2348.35  4442.4 2339.29    4491 2338.18
  4577.7 2337.54    4787 2337.19  4971.6 2335.59  5013.2 2332.29  5013.5 2331.79
  5017.3 2332.29  5022.9 2334.35    5037 2334.92  5193.5 2334.64    5252 2336.19
  5264.3 2334.91  5283.2 2335.94  5309.3 2337.26  5355.1 2335.53  5426.6 2338.05
  5465.1 2335.44  5492.5  2335.8  5567.1 2341.37  5595.6 2346.67  5610.5 2347.16
    5771 2339.65  5891.5 2335.75  5949.1 2336.39  6011.5 2336.38  6267.4 2339.12
#Mann= 12 ,-1 , 0
  3998.7     .07       0  4442.4    .035       0    4491     .07       0
  4577.7    .035       0    4787     .07       0  5013.2     .07       0
  5017.3     .07       0  5283.2    .035       0  5465.1     .07       0
    5771    .035       0  5949.1     .07       0  6011.5    .035       0
Bank Sta=5013.2,5017.3
XS Rating Curve= 0 ,0
Exp/Cntr=0.3,0.1

Type RM Length L Ch R = 1 ,17536   ,246,246,246
BEGIN DESCRIPTION:
Sweetwater Creek Trib 20T2 34.0
END DESCRIPTION:
XS GIS Cut Line= 3
      1380205.01      6820338.01      1381005.08      6821162.96
      1382554.97      6820288.02
#Sta/Elev= 30
  3850.8 2362.66  4020.4 2352.75  4367.7 2339.16  4515.6 2334.53  4584.2 2334.95
  4587.1 2334.95  4763.1 2337.68  4853.3 2336.21  4989.4 2331.37  5016.7 2325.02
  5016.9 2324.52  5020.8 2325.02  5024.4 2326.82  5034.4 2325.75    5062 2328.39
  5077.9 2333.48  5099.6  2334.7  5301.6 2334.97  5347.9 2335.23  5407.2 2332.41
  5413.3 2335.38  5423.1 2336.21  5556.6 2336.41  5628.1 2334.45  5714.8 2339.33
  5809.5  2341.1  6020.6  2334.2  6125.1 2335.68  6501.9 2339.87  6779.8 2351.71
#Mann= 12 ,-1 , 0
  3850.8     .07       0  4367.7    .035       0  4584.2     .07       0
  4587.1    .035       0  4853.3     .07       0  5016.7     .07       0
  5020.8     .07       0  5301.6    .035       0  5556.6     .07       0
  5809.5    .035       0  6020.6     .07       0  6125.1    .035       0
Bank Sta=5016.7,5020.8
XS Rating Curve= 0 ,0
Exp/Cntr=0.3,0.1

Type RM Length L Ch R = 1 ,17290   ,250,250,250
BEGIN DESCRIPTION:
Sweetwater Creek Trib 20T2 4131
END DESCRIPTION:
XS GIS Cut Line= 3
      1380698.24       6821184.8      1380954.94      6821392.97
      1381170.24      6821337.64
#Sta/Elev= 30
  4669.5 2330.22    4698 2329.57  4718.8 2329.63  4726.7 2330.38  4747.5  2328.5
  4776.3 2328.53  4797.1 2327.35  4825.8 2328.91  4840.2 2328.21  4846.6 2326.73
  4932.9 2324.67  4947.3  2322.8  4953.7 2323.09  4961.5  2320.5  4968.1 2316.41
  4980.4 2315.49  4980.7 2314.99  4984.5 2315.49  4988.9 2315.59  4996.8 2317.36
  5002.6 2317.36  5051.7 2325.31  5124.8 2327.49  5154.9  2327.4  5165.5 2329.05
  5185.9 2330.16  5195.9 2329.46  5201.1 2331.05  5216.9 2329.91  5222.3 2328.54
#Mann= 3 ,-1 , 0
  4669.5     .07       0  4980.4     .07       0  4984.5     .07       0
Bank Sta=4980.4,4984.5
XS Rating Curve= 0 ,0
Exp/Cntr=0.3,0.1

Type RM Length L Ch R = 1 ,17040   ,493,493,493
BEGIN DESCRIPTION:
Sweetwater Creek Trib 20T2 33.0
END DESCRIPTION:
XS GIS Cut Line= 3
      1380854.98        6821638.      1380955.44      6821643.18
      1381055.02      6821688.01
#Sta/Elev= 29
  4899.4  2319.1  4901.9  2319.1  4909.4 2318.39  4919.5 2317.97  4929.5 2317.74
  4939.5 2317.34  4949.5 2314.07  4959.5 2312.75  4989.5 2303.59  4995.5 2302.06
  4996.2 2301.77  4996.4 2301.27    5000 2301.27  5000.3 2301.77  5010.5 2301.99
  5019.9 2302.09  5025.4 2301.83  5043.1 2302.97  5048.6 2304.15  5054.3  2307.3
  5058.5 2309.27  5065.3 2312.45  5071.7 2316.01  5077.2 2316.81  5087.2 2317.48
  5094.9  2318.3  5100.3 2317.99  5106.4 2319.07  5109.2 2319.07
#Mann= 4 ,-1 , 0
  4899.4     .07       0  4996.2     .07       0  5000.3     .07       0
  5058.5    .035       0
Bank Sta=4996.2,5000.3
XS Rating Curve= 0 ,0
Exp/Cntr=0.3,0.1

Type RM Length L Ch R = 1 ,16547   ,481,481,481
BEGIN DESCRIPTION:
Sweetwater Creek Trib 20T2 32.0
END DESCRIPTION:
XS GIS Cut Line= 3
      1380655.02      6821888.02      1380804.92      6822087.97
      1380955.02      6822037.99
#Sta/Elev= 30
  4750.1 2313.06  4763.6 2312.81  4771.9 2310.97  4778.2 2312.78  4786.5 2311.92
  4792.8 2313.09  4807.4 2307.73  4828.2 2309.93  4892.8 2304.67  4900.1 2306.43
  4913.6  2305.8    4922 2303.47  4928.2 2303.76  4942.8 2299.48    4950 2298.55
  4986.5 2296.56  4992.8 2294.27  4996.9 2295.45  5002.7 2295.45  5008.5  2292.1
  5008.7  2291.6  5012.6  2292.1  5031.7 2294.74  5063.3 2303.48  5084.4 2307.38
  5105.5 2309.78  5110.7 2308.76    5116 2310.92  5147.6 2312.62  5158.2 2312.52
#Mann= 3 ,-1 , 0
  4750.1     .07       0  5008.5     .07       0  5012.6     .07       0
Bank Sta=5008.5,5012.6
XS Rating Curve= 0 ,0
Exp/Cntr=0.3,0.1

Type RM Length L Ch R = 1 ,16066   ,452,452,452
BEGIN DESCRIPTION:
Sweetwater Creek Trib 20T2 31.0
END DESCRIPTION:
XS GIS Cut Line= 3
      1380754.98      6822487.98      1380855.01        6822553.
      1380955.03      6822487.98
#Sta/Elev= 30
  4880.7 2304.37  4883.7 2304.37  4888.3 2303.03  4894.3 2303.38  4903.4 2301.77
  4909.4 2299.02  4924.5 2298.66  4939.7  2295.6  4952.3 2293.77  4960.8 2292.01
  4966.7 2289.99  4981.9 2287.85    4997 2286.64  5009.7 2286.37    5010 2285.87
  5013.8 2285.87  5014.1 2286.37  5018.1 2287.41  5024.1    2288  5033.3 2292.87
  5039.2 2292.93  5044.7 2294.37  5047.7 2295.15  5054.4 2295.82  5060.3 2295.79
  5069.5 2296.92  5075.5 2296.96  5096.6 2300.67  5111.7 2301.98  5119.3  2302.1
#Mann= 4 ,-1 , 0
  4880.7     .07       0  5009.7     .07       0  5014.1     .07       0
  5044.7    .035       0
Bank Sta=5009.7,5014.1
XS Rating Curve= 0 ,0
Exp/Cntr=0.3,0.1

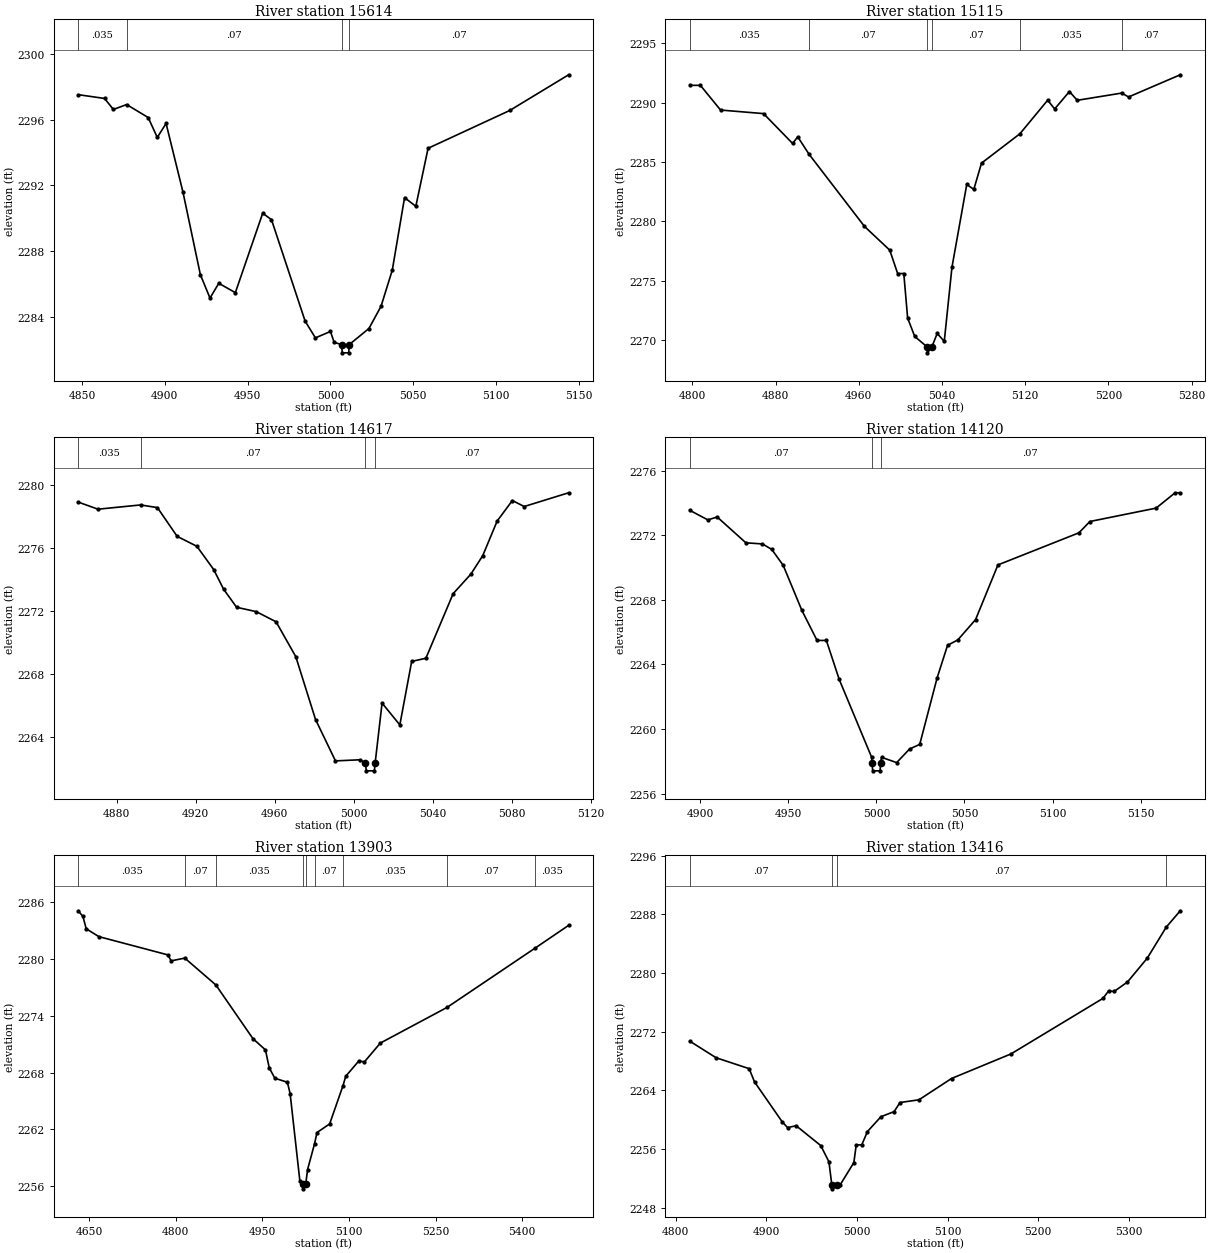
Type RM Length L Ch R = 1 ,15614   ,499,499,499
BEGIN DESCRIPTION:
Sweetwater Creek Trib 20T2 30.0
END DESCRIPTION:
XS GIS Cut Line= 3
      1380804.96      6822887.99      1380949.54      6822935.55
      1381055.03      6822837.97
#Sta/Elev= 30
  4847.8 2297.51  4863.7 2297.28    4869 2296.61    4877 2296.91    4890 2296.12
  4895.5 2294.91  4900.8 2295.76    4911 2291.58  4921.5 2286.56  4927.3 2285.14
  4932.6 2286.04  4942.6 2285.47  4959.1  2290.3  4964.4 2289.91  4984.7 2283.74
  4990.9 2282.72    5000 2283.11  5002.2 2282.45  5006.7 2282.31  5007.1 2281.81
    5011 2281.81  5011.3 2282.31  5023.2 2283.29  5030.5 2284.64  5037.3 2286.84
  5044.7 2291.25  5051.5 2290.72  5058.9 2294.25  5108.2 2296.55  5143.7 2298.72
#Mann= 4 ,-1 , 0
  4847.8    .035       0    4877     .07       0  5006.7     .07       0
  5011.3     .07       0
Bank Sta=5006.7,5011.3
XS Rating Curve= 0 ,0
Exp/Cntr=0.3,0.1

Type RM Length L Ch R = 1 ,15115   ,498,498,498
BEGIN DESCRIPTION:
Sweetwater Creek Trib 20T2 29.0
END DESCRIPTION:
XS GIS Cut Line= 3
        1380805.        6823388.      1381005.07      6823417.97
        1381205.        6823238.
#Sta/Elev= 30
  4797.7 2291.46  4807.8 2291.46  4827.2 2289.38  4868.5 2289.08  4896.4 2286.57
  4901.4 2287.12  4912.3 2285.65  4965.5 2279.58  4989.8 2277.58  4997.4 2275.61
  5003.3 2275.61    5007 2271.86  5013.8 2270.31  5025.7 2269.43    5026 2268.93
  5030.3 2269.43  5035.4 2270.56  5042.2  2269.9  5049.6 2276.14  5063.8 2283.11
  5070.6  2282.7    5078 2284.91  5114.9 2287.38  5141.6 2290.21  5148.3 2289.47
  5162.5 2290.94    5170  2290.2  5212.8 2290.81  5219.3 2290.48    5269 2292.35
#Mann= 6 ,-1 , 0
  4797.7    .035       0  4912.3     .07       0  5025.7     .07       0
  5030.3     .07       0  5114.9    .035       0  5212.8     .07       0
Bank Sta=5025.7,5030.3
XS Rating Curve= 0 ,0
Exp/Cntr=0.3,0.1

Type RM Length L Ch R = 1 ,14617   ,497,497,497
BEGIN DESCRIPTION:
Sweetwater Creek Trib 20T2 28.0
END DESCRIPTION:
XS GIS Cut Line= 3
      1381105.04        6823838.      1381244.21      6823828.33
      1381305.01      6823737.98
#Sta/Elev= 30
  4860.5 2278.89  4870.5 2278.44  4892.1 2278.71  4900.6 2278.54  4910.6 2276.72
  4920.6 2276.09  4929.1 2274.62  4934.1 2273.38  4940.7 2272.23  4950.7 2271.95
  4960.7 2271.31  4970.7  2269.1  4980.7 2265.12  4990.8  2262.5  5003.2 2262.57
    5006 2262.37  5006.4 2261.87  5010.5 2261.87  5010.9 2262.37  5014.4 2266.16
  5023.4 2264.78  5029.4  2268.8  5036.6    2269  5050.4 2273.09  5059.4 2274.33
  5065.4  2275.5  5072.7 2277.69  5080.4 2278.99  5086.4 2278.61  5108.9 2279.48
#Mann= 4 ,-1 , 0
  4860.5    .035       0  4892.1     .07       0    5006     .07       0
  5010.9     .07       0
Bank Sta=5006,5010.9
XS Rating Curve= 0 ,0
Exp/Cntr=0.3,0.1

Type RM Length L Ch R = 1 ,14120   ,217,217,217
BEGIN DESCRIPTION:
Sweetwater Creek Trib 20T2 27.0
END DESCRIPTION:
XS GIS Cut Line= 3
      1381155.01        6824288.      1381254.96      6824323.02
      1381405.04      6824237.98
#Sta/Elev= 30
  4894.1 2273.55  4904.3 2272.96  4909.6 2273.14  4925.9 2271.54  4935.3 2271.47
  4940.6 2271.13  4947.1 2270.14  4957.7 2267.35  4966.3 2265.49  4971.6 2265.49
  4978.9 2263.07  4997.3 2258.25  4997.5 2257.91  4997.9 2257.41  5002.1 2257.41
  5002.4 2257.91  5002.9 2258.25  5011.5 2257.92  5018.8 2258.76  5024.6 2259.05
  5034.5 2263.18  5040.4 2265.19  5046.2 2265.52  5056.3 2266.78    5069 2270.17
    5115 2272.16  5121.2 2272.86  5158.8 2273.69  5169.6 2274.64  5172.5 2274.64
#Mann= 3 ,-1 , 0
  4894.1     .07       0  4997.5     .07       0  5002.4     .07       0
Bank Sta=4997.5,5002.4
XS Rating Curve= 0 ,0
Exp/Cntr=0.3,0.1

Type RM Length L Ch R = 1 ,13903   ,487,487,487
BEGIN DESCRIPTION:
Sweetwater Creek Trib 20T2 26.0
END DESCRIPTION:
XS GIS Cut Line= 3
      1381004.98      6824688.01      1381328.27      6824511.36
      1381555.02      6824087.96
#Sta/Elev= 30
  4631.6 2285.09  4639.7 2284.49  4645.4 2283.19  4667.2 2282.36  4786.7 2280.43
  4792.4  2279.8    4816 2280.09  4869.8 2277.25  4933.8 2271.59  4955.6 2270.39
  4962.1  2268.5  4971.8  2267.4  4993.6 2266.97  4998.3 2265.77  5015.2 2256.52
  5020.3 2256.21  5020.7 2255.71  5025.3 2256.21  5028.5 2257.75  5040.6 2260.48
  5044.8 2261.66  5066.7 2262.57  5089.8 2266.61  5094.6 2267.61  5117.3 2269.23
  5126.8 2269.12  5154.4 2271.11  5269.9 2274.88  5422.4 2281.15  5480.3 2283.55
#Mann= 9 ,-1 , 0
  4631.6    .035       0    4816     .07       0  4869.8    .035       0
  5020.3    .035       0  5025.3    .035       0  5040.6     .07       0
  5089.8    .035       0  5269.9     .07       0  5422.4    .035       0
Bank Sta=5020.3,5025.3
XS Rating Curve= 0 ,0
Exp/Cntr=0.3,0.1

Type RM Length L Ch R = 1 ,13416   ,497,497,497
BEGIN DESCRIPTION:
Sweetwater Creek Trib 20T2 25.0
END DESCRIPTION:
XS GIS Cut Line= 3
      1381455.01      6824987.99       1381611.1      6824890.19
      1381904.98      6824688.02
#Sta/Elev= 30
  4815.8 2270.71  4844.7 2268.46  4881.2 2266.97  4887.1 2265.17  4917.7 2259.72
  4923.6 2258.94    4933  2259.2  4960.2 2256.49  4969.2 2254.28  4972.4  2251.1
  4972.9  2250.6  4978.5  2251.1  4981.4 2251.11  4996.7 2254.18  4999.3 2256.59
  5005.4 2256.59  5011.7 2258.41  5026.6 2260.43  5041.1 2261.12  5047.6 2262.36
  5068.5 2262.73  5104.4 2265.63    5170 2268.98  5271.5 2276.55  5277.6 2277.55
  5283.9  2277.5  5298.5 2278.78  5320.3 2282.02  5341.2 2286.24  5356.7 2288.48
#Mann= 4 ,-1 , 0
  4815.8     .07       0  4972.4     .07       0  4978.5     .07       0
  5341.2    .035       0
Bank Sta=4972.4,4978.5
XS Rating Curve= 0 ,0
Exp/Cntr=0.3,0.1

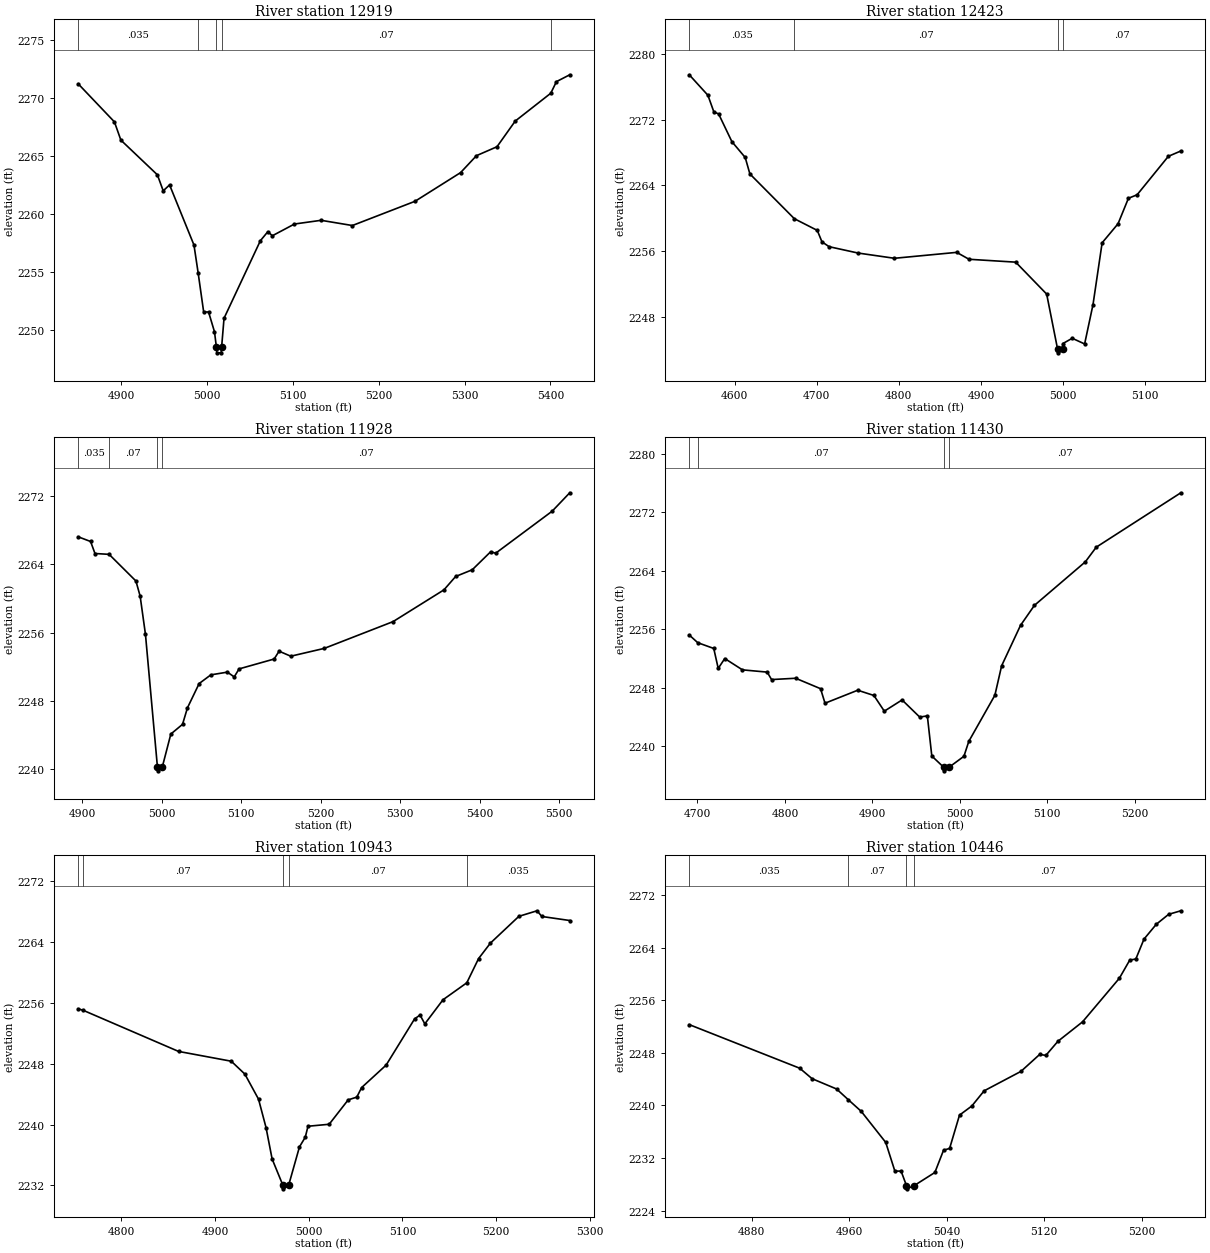
Type RM Length L Ch R = 1 ,12919   ,496,496,496
BEGIN DESCRIPTION:
Sweetwater Creek Trib 20T2 24.0
END DESCRIPTION:
XS GIS Cut Line= 3
      1381754.99      6825388.01      1381865.48      6825286.85
      1382004.98      6824888.04
#Sta/Elev= 30
  4850.2  2271.2  4892.4 2267.92  4899.9 2266.35  4942.4 2263.36  4949.2 2261.98
  4956.6 2262.49    4985 2257.31  4989.8 2254.94  4996.3 2251.54    5002 2251.54
  5008.9 2249.83  5011.1 2248.52  5011.6 2248.02  5016.7 2248.02  5017.2 2248.52
    5020    2251  5062.3 2257.68    5071 2258.46  5076.3 2258.11    5102 2259.12
    5133 2259.44  5169.4 2258.99  5242.4 2261.08  5295.4 2263.55  5313.9 2265.01
  5337.8 2265.78    5359 2267.99  5400.4 2270.39    5407 2271.39  5422.5 2271.98
#Mann= 5 ,-1 , 0
  4850.2    .035       0  4989.8     .07       0  5011.1     .07       0
  5017.2     .07       0  5400.4    .035       0
Bank Sta=5011.1,5017.2
XS Rating Curve= 0 ,0
Exp/Cntr=0.3,0.1

Type RM Length L Ch R = 1 ,12423   ,495,495,495
BEGIN DESCRIPTION:
Sweetwater Creek Trib 20T2 23.0
END DESCRIPTION:
XS GIS Cut Line= 3
      1382055.02      6825537.96      1382270.43      6825137.07
      1382404.97      6825088.01
#Sta/Elev= 30
  4544.9 2277.44  4567.6 2274.95  4574.9 2272.91  4580.6 2272.69  4596.8 2269.31
    4613 2267.39  4618.7 2265.39  4672.8 2259.95  4700.7 2258.53  4706.4 2257.14
  4715.1 2256.55  4750.2 2255.78  4794.6 2255.14  4870.4 2255.86  4885.4 2255.02
  4942.2 2254.67  4979.9 2250.79  4993.1 2244.15  4993.6 2243.65  4999.3 2244.15
  4999.5 2244.77    5011 2245.42  5026.1 2244.73  5036.3 2249.51  5047.4 2257.02
  5066.8 2259.34  5079.4 2262.43    5090 2262.86    5128 2267.53  5143.2 2268.18
#Mann= 4 ,-1 , 0
  4544.9    .035       0  4672.8     .07       0  4993.1     .07       0
  4999.3     .07       0
Bank Sta=4993.1,4999.3
XS Rating Curve= 0 ,0
Exp/Cntr=0.3,0.1

Type RM Length L Ch R = 1 ,11928   ,498,498,498
BEGIN DESCRIPTION:
Sweetwater Creek Trib 20T2 22.0
END DESCRIPTION:
XS GIS Cut Line= 3
      1382155.03      6825587.99      1382254.26      6825553.68
      1382555.02      6825137.97
#Sta/Elev= 30
    4895 2267.25  4910.6  2266.7  4916.1 2265.29  4933.9 2265.19  4967.6 2262.06
  4972.9 2260.29  4979.6 2255.79  4994.6 2240.27  4995.1 2239.77  5000.9 2240.27
  5011.5 2244.09  5026.2 2245.23  5032.4 2247.17  5047.1 2250.02  5061.8 2251.04
  5082.6 2251.36  5091.2  2250.8  5097.3 2251.74  5141.4  2252.9  5147.6 2253.82
  5162.3 2253.23  5204.5 2254.15  5290.9 2257.29  5354.9 2261.02  5369.6 2262.59
  5390.5 2263.38  5413.7  2265.5  5419.9 2265.32    5491 2270.26  5513.1 2272.42
#Mann= 4 ,-1 , 0
    4895    .035       0  4933.9     .07       0  4994.6     .07       0
  5000.9     .07       0
Bank Sta=4994.6,5000.9
XS Rating Curve= 0 ,0
Exp/Cntr=0.3,0.1

Type RM Length L Ch R = 1 ,11430   ,487,487,487
BEGIN DESCRIPTION:
Sweetwater Creek Trib 20T2 21.0
END DESCRIPTION:
XS GIS Cut Line= 3
      1382404.99        6825688.      1382710.24      6825637.51
      1382930.01      6825512.98
#Sta/Elev= 30
  4690.6 2255.19  4700.3 2254.14  4718.6 2253.35  4723.7 2250.62  4731.2 2251.97
  4751.4 2250.42  4779.7 2250.11  4784.7 2249.09  4812.2 2249.27  4840.7 2247.84
  4845.8 2245.85  4883.2 2247.63  4901.7 2246.91  4913.6 2244.76  4933.9  2246.3
  4954.1 2243.95  4962.8 2244.12  4967.9 2238.62  4981.4 2237.09  4981.9 2236.59
  4987.7 2237.09  5004.6 2238.58  5010.2 2240.63    5040 2246.94  5047.7 2250.97
  5069.3 2256.51  5085.2 2259.25  5143.4 2265.21  5155.9 2267.22  5252.6 2274.67
#Mann= 4 ,-1 , 0
  4690.6    .035       0  4700.3     .07       0  4981.4     .07       0
  4987.7     .07       0
Bank Sta=4981.4,4987.7
XS Rating Curve= 0 ,0
Exp/Cntr=0.3,0.1

Type RM Length L Ch R = 1 ,10943   ,497,497,497
BEGIN DESCRIPTION:
Sweetwater Creek Trib 20T2 20.0
END DESCRIPTION:
XS GIS Cut Line= 3
      1382405.02      6825738.02      1382553.42      6825934.34
      1382828.61      6825977.78
#Sta/Elev= 30
  4753.9 2255.23  4759.5 2255.02    4861 2249.63  4917.3 2248.34  4931.8 2246.65
  4946.4 2243.35  4954.4 2239.62  4960.9 2235.49  4972.3 2232.06  4972.8 2231.56
  4978.6 2232.06  4990.1 2237.08  4996.3 2238.35  4999.2 2239.79  5021.8 2240.05
  5042.1 2243.26  5051.3 2243.62  5056.4 2244.87  5082.6 2247.83    5113 2253.91
  5118.8 2254.41  5123.9 2253.25  5143.3 2256.42  5168.7 2258.65  5181.3 2261.84
    5194 2263.88  5224.3 2267.39  5243.7 2268.12  5248.8 2267.37  5278.6 2266.84
#Mann= 5 ,-1 , 0
  4753.9    .035       0  4759.5     .07       0  4972.3     .07       0
  4978.6     .07       0  5168.7    .035       0
Bank Sta=4972.3,4978.6
XS Rating Curve= 0 ,0
Exp/Cntr=0.3,0.1

Type RM Length L Ch R = 1 ,10446   ,488,488,488
BEGIN DESCRIPTION:
Sweetwater Creek Trib 20T2 19.0
END DESCRIPTION:
XS GIS Cut Line= 3
      1382304.98        6826338.      1382474.92      6826318.11
      1382704.96      6826288.01
#Sta/Elev= 30
  4828.9 2252.31  4919.5 2245.67  4929.6 2244.08  4949.7 2242.51  4959.3 2240.88
  4969.9 2239.11    4990 2234.38  4997.5 2230.01  5002.6 2230.01    5007 2227.81
  5007.5 2227.31  5013.4 2227.81  5030.3  2229.8  5037.4 2233.18  5042.4 2233.47
  5050.5 2238.53  5060.6 2239.92  5070.7 2242.23  5100.9 2245.19  5116.3 2247.78
  5121.3 2247.62  5131.2 2249.77  5151.4 2252.73  5181.6 2259.37  5190.1 2262.13
  5195.1  2262.3  5201.8 2265.33  5211.9 2267.59    5222  2269.1    5232 2269.64
#Mann= 4 ,-1 , 0
  4828.9    .035       0  4959.3     .07       0    5007     .07       0
  5013.4     .07       0
Bank Sta=5007,5013.4
XS Rating Curve= 0 ,0
Exp/Cntr=0.3,0.1

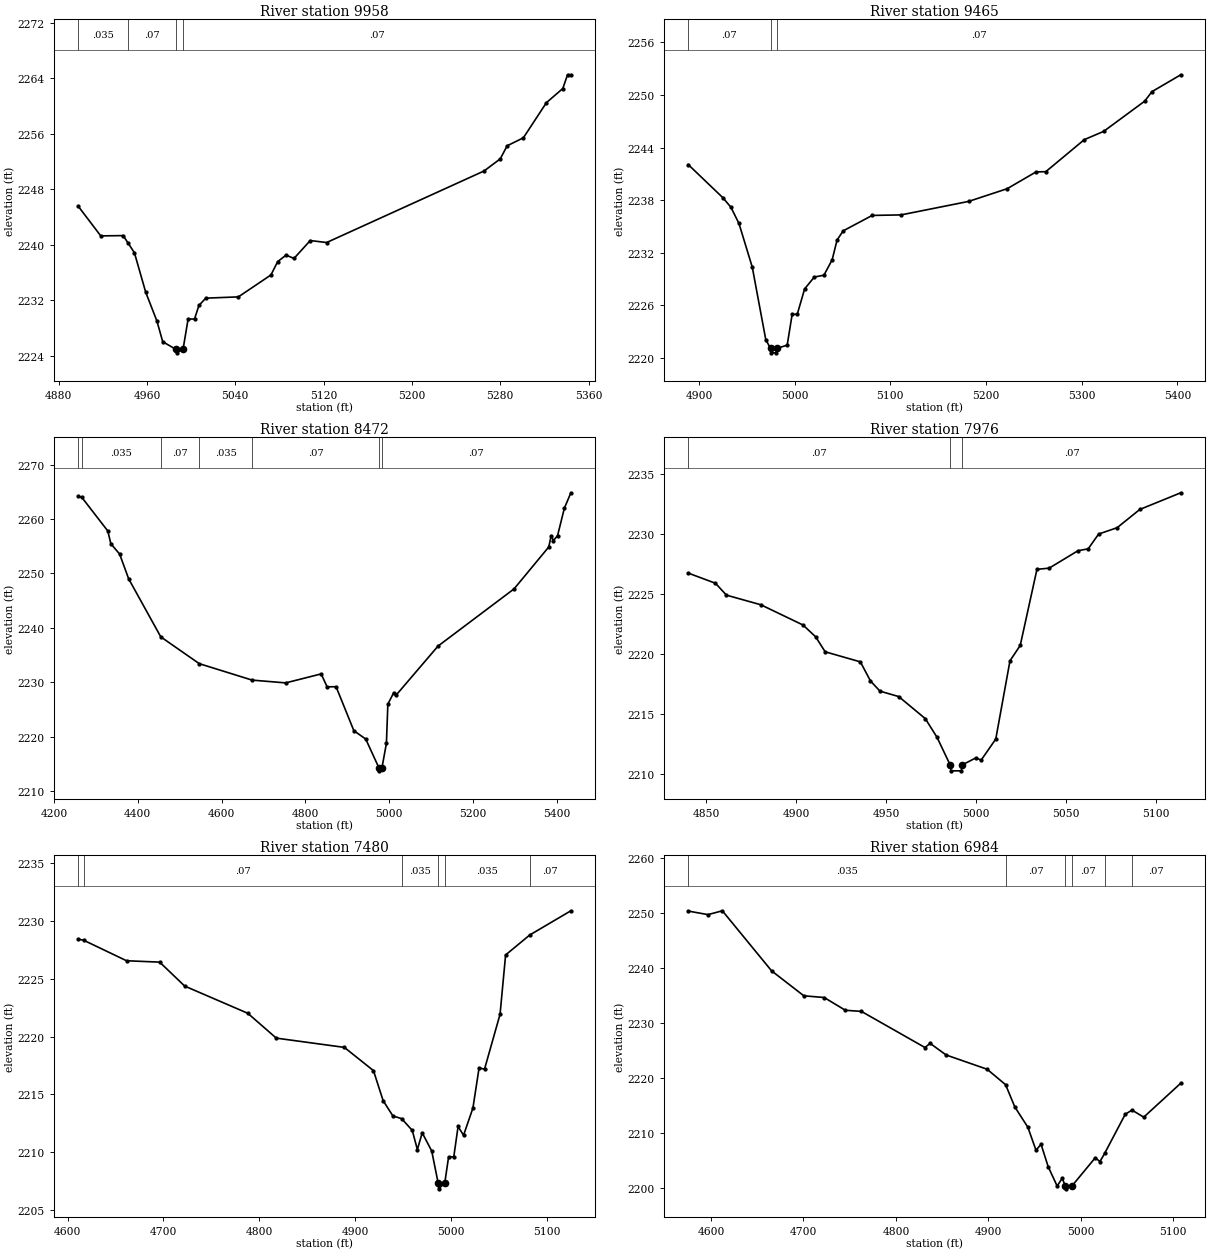
Type RM Length L Ch R = 1 ,9958    ,493,493,493
BEGIN DESCRIPTION:
Sweetwater Creek Trib 20T2 18.0
END DESCRIPTION:
XS GIS Cut Line= 3
      1382455.04      6826787.99      1382555.27      6826767.98
      1382754.98      6826488.02
#Sta/Elev= 30
  4897.8 2245.57  4918.2  2241.3  4938.5 2241.34    4943 2240.25  4948.7 2238.86
  4958.9 2233.18  4969.1 2229.01  4974.3 2226.05  4986.3 2224.95  4986.8 2224.45
  4992.7 2224.95  4997.3 2229.32  5003.1 2229.32  5007.1 2231.28  5013.3 2232.33
  5042.8 2232.51  5072.3 2235.67  5078.4 2237.59    5086 2238.53  5093.2 2238.05
  5107.9 2240.63  5122.7 2240.34  5265.3 2250.65    5280  2252.4  5286.2 2254.28
  5300.9 2255.43  5321.8  2260.5  5336.6 2262.53  5340.9 2264.51  5343.9 2264.51
#Mann= 4 ,-1 , 0
  4897.8    .035       0    4943     .07       0  4986.3     .07       0
  4992.7     .07       0
Bank Sta=4986.3,4992.7
XS Rating Curve= 0 ,0
Exp/Cntr=0.3,0.1

Type RM Length L Ch R = 1 ,9465    ,993,993,993
BEGIN DESCRIPTION:
Sweetwater Creek Trib 20T2 17.0
END DESCRIPTION:
XS GIS Cut Line= 3
      1382805.02      6827187.96      1382854.66      6827088.35
        1382905.        6826688.
#Sta/Elev= 30
  4888.7 2242.06    4925 2238.27  4933.4 2237.18  4941.8 2235.33  4955.7 2230.35
  4969.8 2222.08  4974.8 2221.07  4975.3 2220.57  4980.7 2220.57  4981.2 2221.07
  4992.2 2221.45  4997.4 2224.97  5002.7 2224.97  5010.4 2227.86  5020.5 2229.22
  5030.6 2229.43  5039.2 2231.19  5044.3 2233.44  5050.7 2234.49    5081 2236.25
  5111.2 2236.31  5181.8 2237.85  5222.1  2239.3  5252.3 2241.22  5262.4 2241.24
  5302.7  2244.9  5322.9 2245.84  5365.8 2249.29  5373.3 2250.37  5403.5  2252.3
#Mann= 3 ,-1 , 0
  4888.7     .07       0  4974.8     .07       0  4981.2     .07       0
Bank Sta=4974.8,4981.2
XS Rating Curve= 0 ,0
Exp/Cntr=0.3,0.1

Type RM Length L Ch R = 1 ,8472    ,496,496,496
BEGIN DESCRIPTION:
Sweetwater Creek Trib 20T2 16.0
END DESCRIPTION:
XS GIS Cut Line= 3
      1383105.01      6827387.99      1383614.71      6826848.75
      1383754.98      6826438.05
#Sta/Elev= 30
    4258  2264.2  4266.6 2263.98  4328.6 2257.81  4335.9 2255.46  4356.9 2253.56
  4378.3 2249.03  4455.1 2238.35    4547 2233.43  4673.1 2230.41  4753.3  2229.9
  4837.9 2231.55  4852.1 2229.17  4873.5  2229.2    4916 2221.11  4944.3 2219.58
  4976.1 2214.24  4976.6 2213.74  4982.9 2214.24  4993.7  2218.8  4997.1 2225.99
  5011.2 2228.11  5016.5 2227.62    5117 2236.67  5298.4 2247.17  5381.2 2254.87
  5387.1 2256.96  5392.4 2256.04  5402.3 2256.97  5418.4 2261.98    5434 2264.83
#Mann= 7 ,-1 , 0
    4258     .07       0  4266.6    .035       0  4455.1     .07       0
    4547    .035       0  4673.1     .07       0  4976.1     .07       0
  4982.9     .07       0
Bank Sta=4976.1,4982.9
XS Rating Curve= 0 ,0
Exp/Cntr=0.3,0.1

Type RM Length L Ch R = 1 ,7976    ,496,496,496
BEGIN DESCRIPTION:
Sweetwater Creek Trib 20T2 15.0
END DESCRIPTION:
XS GIS Cut Line= 3
      1383605.04      6827238.01      1383755.44      6827293.18
      1383854.97      6827238.01
#Sta/Elev= 30
  4839.8 2226.71    4855 2225.86  4861.1 2224.87  4880.2 2224.07  4903.7 2222.38
  4910.7  2221.4    4916 2220.15  4935.6 2219.31  4941.2 2217.72  4946.5 2216.87
  4956.9 2216.42  4971.7 2214.58  4978.2 2213.03  4985.5 2210.73    4986 2210.23
  4991.8 2210.23  4992.3 2210.73  4999.7  2211.3  5002.8 2211.13  5010.9 2212.88
  5018.8  2219.4  5024.5 2220.68  5033.8 2227.02  5040.6 2227.12  5056.6 2228.57
  5062.3 2228.73  5068.1 2229.96  5078.4 2230.49    5091 2232.01  5113.8  2233.4
#Mann= 3 ,-1 , 0
  4839.8     .07       0  4985.5     .07       0  4992.3     .07       0
Bank Sta=4985.5,4992.3
XS Rating Curve= 0 ,0
Exp/Cntr=0.3,0.1

Type RM Length L Ch R = 1 ,7480    ,496,496,496
BEGIN DESCRIPTION:
Sweetwater Creek Trib 20T2 14.0
END DESCRIPTION:
XS GIS Cut Line= 3
      1383481.53      6827294.15      1383545.72      6827677.62
        1383605.        6827788.
#Sta/Elev= 30
  4611.2 2228.42  4616.7 2228.34  4661.6 2226.56  4696.2 2226.44  4722.3 2224.37
  4788.1 2222.02  4817.9 2219.87  4888.9 2219.07  4919.3 2217.06  4929.4 2214.46
  4939.6 2213.14  4948.7 2212.91  4959.8 2211.89  4965.1 2210.24  4970.2 2211.68
  4980.1 2210.11  4986.8 2207.34  4987.3 2206.84  4993.7 2207.34  4997.7  2209.6
  5003.1  2209.6  5007.6 2212.23  5013.3 2211.47  5023.1 2213.83  5029.5 2217.29
  5035.2 2217.19  5051.4 2221.93  5057.2 2227.06  5082.3 2228.78  5125.3 2230.88
#Mann= 6 ,-1 , 0
  4611.2    .035       0  4616.7     .07       0  4948.7    .035       0
  4986.8    .035       0  4993.7    .035       0  5082.3     .07       0
Bank Sta=4986.8,4993.7
XS Rating Curve= 0 ,0
Exp/Cntr=0.3,0.1

Type RM Length L Ch R = 1 ,6984    ,497,497,497
BEGIN DESCRIPTION:
Sweetwater Creek Trib 20T2 13.0
END DESCRIPTION:
XS GIS Cut Line= 3
      1382961.41       6827653.5      1383346.91      6827831.97
      1383455.04        6827838.
#Sta/Elev= 30
  4575.2 2250.39  4596.7 2249.74  4612.2 2250.44  4665.5 2239.51  4700.4 2234.97
  4722.4 2234.66  4745.3 2232.34  4762.7 2232.13  4831.5 2225.56    4837 2226.32
  4854.4  2224.2  4898.7 2221.61  4918.7  2218.8  4928.7 2214.75  4942.8 2211.06
  4951.6 2206.88  4957.1 2207.95  4964.8 2203.88  4974.5 2200.36    4980 2201.78
  4983.4 2200.35  4983.9 2199.85  4990.4 2200.35  5015.8 2205.51  5020.8  2204.8
  5026.2 2206.39  5048.2 2213.42  5055.5 2214.18  5068.2 2212.89  5108.3 2219.07
#Mann= 6 ,-1 , 0
  4575.2    .035       0  4918.7     .07       0  4983.4     .07       0
  4990.4     .07       0  5026.2    .035       0  5055.5     .07       0
Bank Sta=4983.4,4990.4
XS Rating Curve= 0 ,0
Exp/Cntr=0.3,0.1