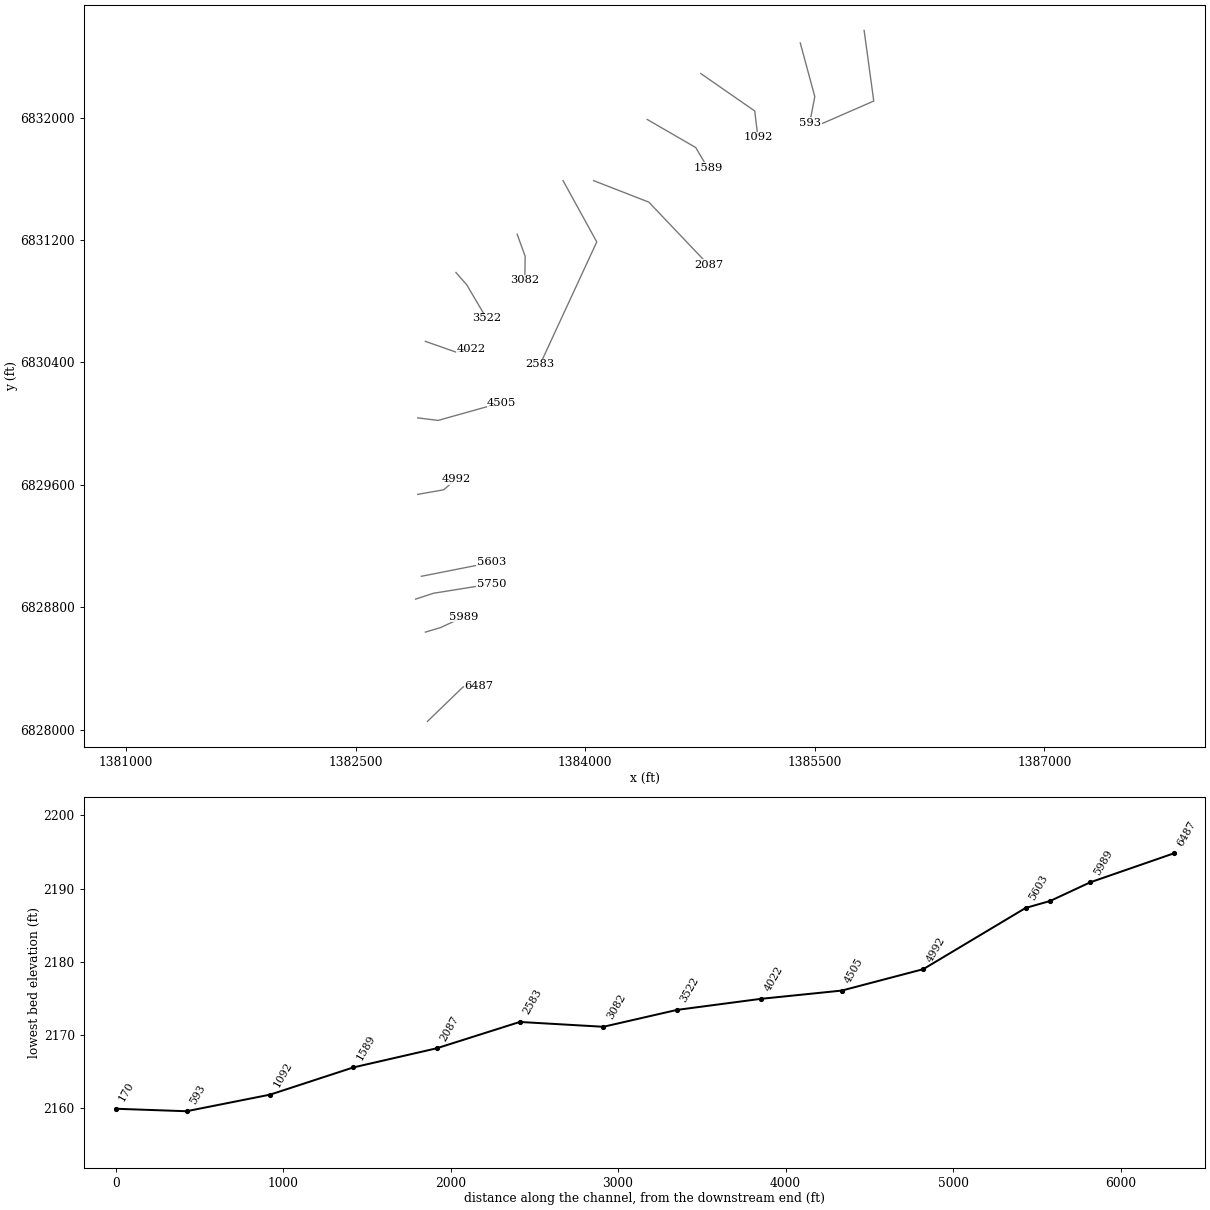
HEC-RAS study Sweetwater Creek Trib 20T2.prj: Sweetwater Creek Trib 20T2 Base Level Engineering

--- Sweetwater Creek Trib 20T2.g01 (geometry) --- (continued)

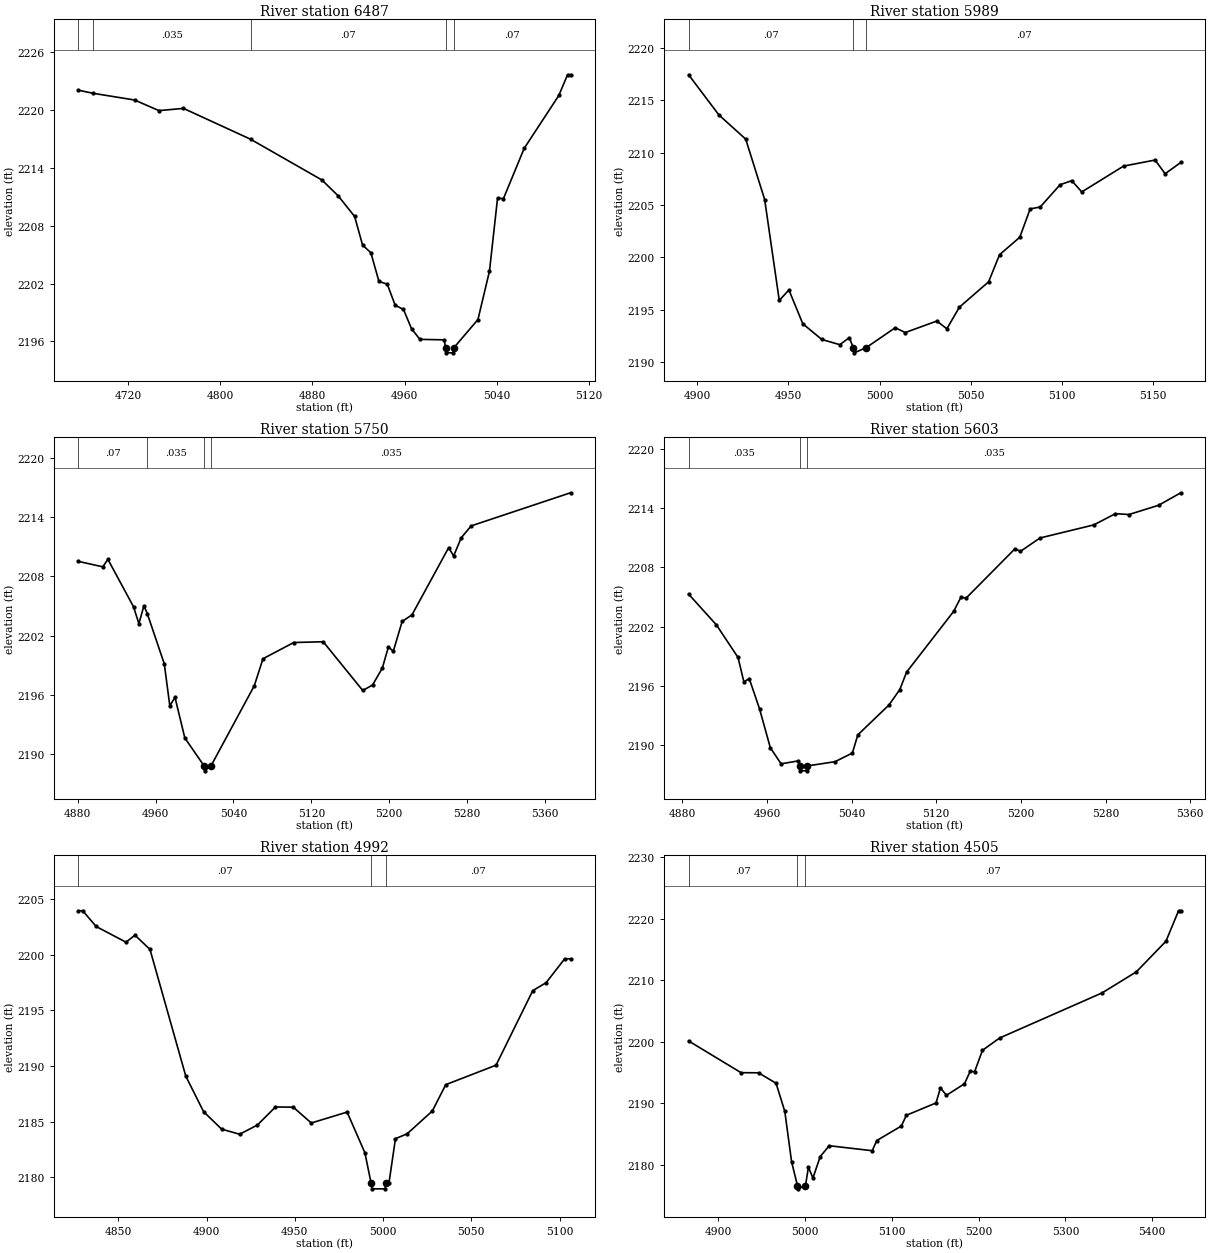
Type RM Length L Ch R = 1 ,6487    ,498,498,498
BEGIN DESCRIPTION:
Sweetwater Creek Trib 20T2 12.0
END DESCRIPTION:
XS GIS Cut Line= 3
       1382969.2      6828054.94      1383201.49      6828279.52
      1383305.04        6828288.
#Sta/Elev= 30
  4676.9 2222.08  4689.6 2221.76  4725.7 2221.06  4746.8 2219.96  4768.1 2220.19
  4826.3 2216.99  4888.3 2212.75  4902.4  2211.1  4916.6 2208.97  4923.5    2206
  4930.7  2205.2  4937.7 2202.22  4944.9 2201.94  4951.8 2199.75    4959 2199.31
    4966 2197.31  4973.2 2196.21  4994.3 2196.16  4995.5 2195.31    4996 2194.81
    5002 2194.81  5002.5 2195.31  5023.6 2198.27  5033.6  2203.3  5040.6 2210.88
  5045.7 2210.82  5063.7 2216.04  5093.8 2221.54  5101.3 2223.68  5103.9 2223.68
#Mann= 5 ,-1 , 0
  4676.9     .07       0  4689.6    .035       0  4826.3     .07       0
  4995.5     .07       0  5002.5     .07       0
Bank Sta=4995.5,5002.5
XS Rating Curve= 0 ,0
Exp/Cntr=0.3,0.1

Type RM Length L Ch R = 1 ,5989    ,239,239,239
BEGIN DESCRIPTION:
Sweetwater Creek Trib 20T2 11.0
END DESCRIPTION:
XS GIS Cut Line= 3
      1382955.03      6828638.01      1383055.38      6828667.86
      1383204.96      6828737.98
#Sta/Elev= 30
  4895.3 2217.44  4911.9  2213.6  4926.6 2211.29    4937 2205.51    4945 2195.87
  4950.3 2196.87  4957.9 2193.64  4968.3 2192.14  4978.2 2191.64  4983.4 2192.31
  4985.6 2191.36  4986.1 2190.86  4992.7 2191.36  5008.6 2193.26  5014.1  2192.8
  5031.4  2193.9  5036.9 2193.16  5043.8 2195.23  5059.8 2197.65  5065.8 2200.24
  5076.9 2201.91  5082.6 2204.62  5088.1  2204.8    5099 2206.93  5105.4 2207.32
  5110.9 2206.24  5133.8 2208.71  5151.1 2209.29  5156.6 2207.98  5165.2 2209.06
#Mann= 3 ,-1 , 0
  4895.3     .07       0  4985.6     .07       0  4992.7     .07       0
Bank Sta=4985.6,4992.7
XS Rating Curve= 0 ,0
Exp/Cntr=0.3,0.1

Type RM Length L Ch R = 1 ,5750    ,147,147,147
BEGIN DESCRIPTION:
Sweetwater Creek Trib 20T2 4185
END DESCRIPTION:
XS GIS Cut Line= 3
      1382891.09      6828853.55      1383007.37      6828891.73
      1383385.84      6828952.49
#Sta/Elev= 30
  4880.6  2209.5  4905.7 2208.95    4911  2209.7  4937.3 2204.91  4942.8  2203.2
    4948 2205.01  4951.5  2204.2  4968.9 2199.14  4974.6 2194.88  4979.9 2195.75
    4990 2191.64  5009.8 2188.81  5010.3 2188.31  5016.9 2188.81  5061.4 2196.92
  5070.3 2199.65  5101.9 2201.29  5132.2 2201.37  5172.8 2196.44  5182.9 2196.99
    5193 2198.72  5199.2 2200.85  5204.2  2200.4  5213.3 2203.42  5223.4 2204.09
  5261.1 2210.89  5266.2 2210.05    5274 2211.88  5284.2 2213.09  5386.3 2216.44
#Mann= 4 ,-1 , 0
  4880.6     .07       0  4951.5    .035       0  5009.8    .035       0
  5016.9    .035       0
Bank Sta=5009.8,5016.9
XS Rating Curve= 0 ,0
Exp/Cntr=0.3,0.1

Type RM Length L Ch R = 1 ,5603    ,611,611,611
BEGIN DESCRIPTION:
Sweetwater Creek Trib 20T2 10.0
END DESCRIPTION:
XS GIS Cut Line= 3
      1382929.22      6829002.83      1383041.17      6829024.87
      1383385.59      6829093.06
#Sta/Elev= 30
  4885.9 2205.29  4912.2 2202.16  4932.6 2198.86  4938.1 2196.39  4943.2 2196.71
  4952.9 2193.65  4963.1  2189.7  4973.3 2188.06  4989.5 2188.36    4991 2187.85
  4991.5 2187.35  4997.6 2187.35  4998.1 2187.85  5024.3 2188.28  5040.7 2189.16
  5045.8    2191  5075.3 2194.04  5085.5  2195.6  5091.9 2197.37  5136.4 2203.54
  5143.2 2204.96  5148.3  2204.9  5194.4  2209.9  5199.5 2209.63    5218 2210.99
  5268.9 2212.32  5289.3 2213.46    5302 2213.37  5330.1 2214.31  5351.1 2215.58
#Mann= 3 ,-1 , 0
  4885.9    .035       0    4991    .035       0  4998.1    .035       0
Bank Sta=4991,4998.1
XS Rating Curve= 0 ,0
Exp/Cntr=0.3,0.1

Type RM Length L Ch R = 1 ,4992    ,487,487,487
BEGIN DESCRIPTION:
Sweetwater Creek Trib 20T2 9.0
END DESCRIPTION:
XS GIS Cut Line= 3
      1382905.04      6829538.01      1383075.11      6829568.04
        1383155.        6829638.
#Sta/Elev= 30
  4827.3 2203.94  4829.8 2203.94  4837.4 2202.53  4854.3 2201.12  4859.4 2201.75
  4867.9 2200.47  4888.2 2189.09  4898.3  2185.9  4908.5 2184.34  4918.7 2183.88
  4928.8 2184.71    4939 2186.33  4949.1 2186.31  4959.3 2184.89  4979.6 2185.87
  4989.7 2182.21  4993.2 2179.48  4993.7 2178.98  5001.1 2178.98  5001.6 2179.48
  5003.3 2179.48    5007 2183.48  5013.7 2183.93  5027.9 2185.97  5035.5 2188.33
    5064 2190.08  5084.8 2196.77  5092.4 2197.49  5102.9 2199.63  5106.2 2199.63
#Mann= 3 ,-1 , 0
  4827.3     .07       0  4993.2     .07       0  5001.6     .07       0
Bank Sta=4993.2,5001.6
XS Rating Curve= 0 ,0
Exp/Cntr=0.3,0.1

Type RM Length L Ch R = 1 ,4505    ,483,483,483
BEGIN DESCRIPTION:
Sweetwater Creek Trib 20T2 8.0
END DESCRIPTION:
XS GIS Cut Line= 3
      1382905.04      6830037.99      1383038.11      6830021.42
      1383455.02      6830138.01
#Sta/Elev= 30
  4865.9  2200.1  4926.3 2194.94  4946.5 2194.92  4966.6 2193.22  4976.7 2188.64
  4984.5 2180.46  4991.3 2176.55  4991.8 2176.05  5000.5 2176.55  5003.9 2179.58
  5009.1 2177.81  5017.5  2181.3  5027.9 2183.06  5077.4 2182.25  5082.6  2183.9
    5111 2186.27  5116.7 2188.01  5150.9 2190.02    5156 2192.47  5162.9 2191.26
  5183.7 2193.14  5190.2 2195.15  5195.4 2195.11  5204.4 2198.58  5224.3 2200.59
  5342.3 2207.92  5381.7 2211.34  5415.8 2216.32  5430.3 2221.27  5432.9 2221.27
#Mann= 3 ,-1 , 0
  4865.9     .07       0  4991.3     .07       0  5000.5     .07       0
Bank Sta=4991.3,5000.5
XS Rating Curve= 0 ,0
Exp/Cntr=0.3,0.1

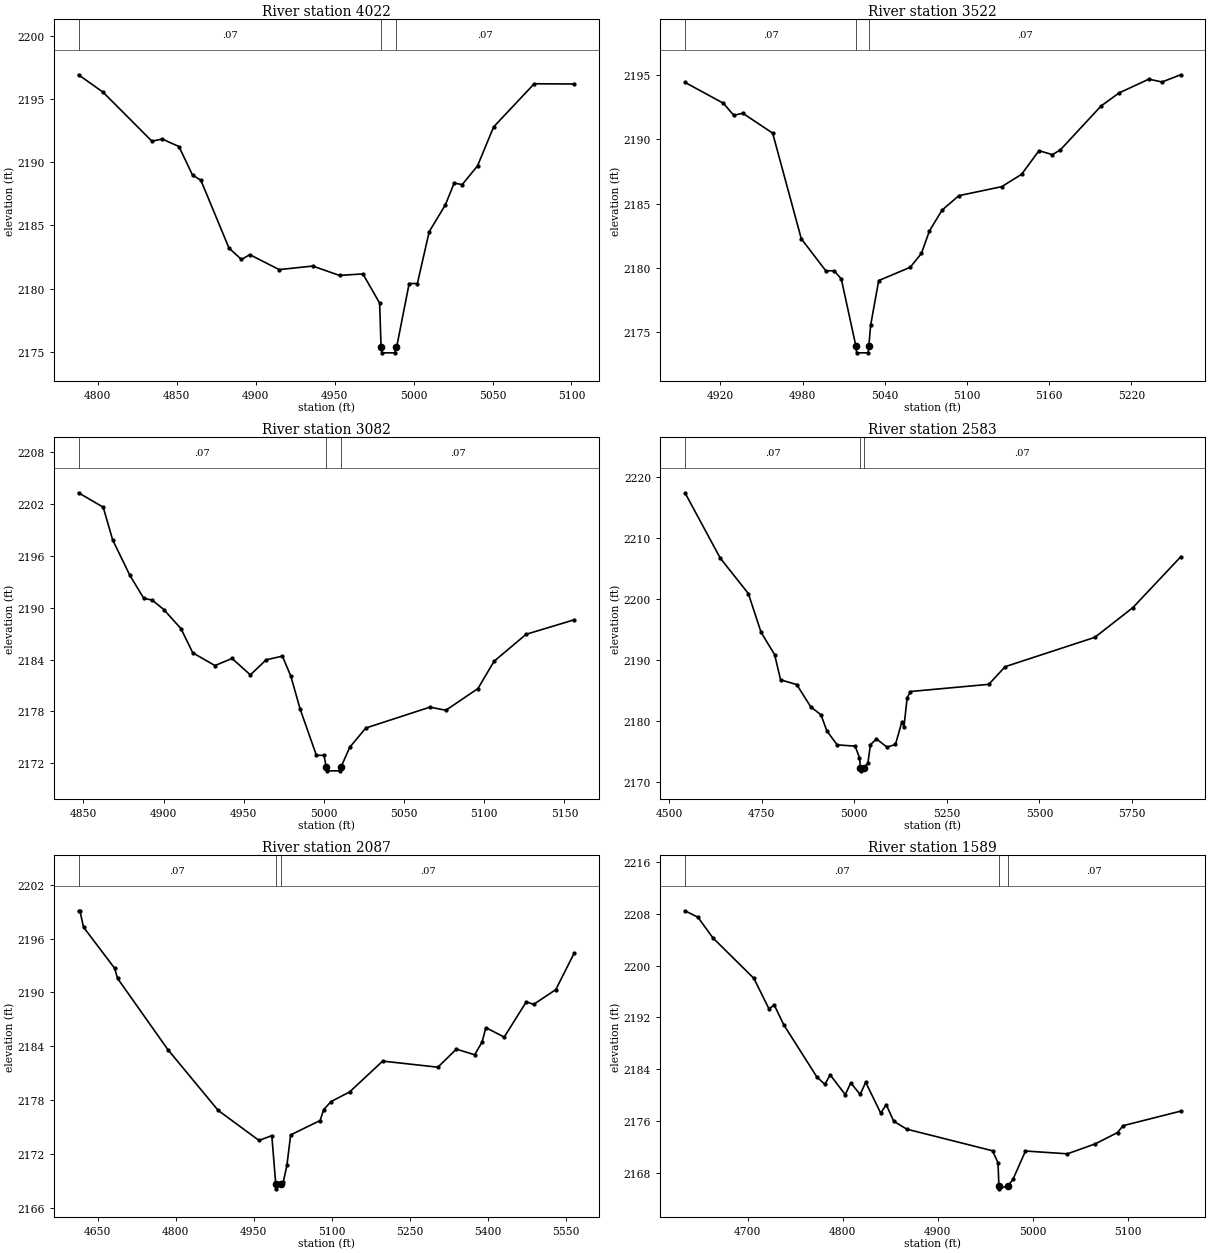
Type RM Length L Ch R = 1 ,4022    ,500,500,500
BEGIN DESCRIPTION:
Sweetwater Creek Trib 20T2 7.0
END DESCRIPTION:
XS GIS Cut Line= 3
      1382955.02      6830537.99      1383155.28      6830467.82
      1383254.96      6830487.99
#Sta/Elev= 30
  4787.8  2196.9  4803.3 2195.53  4834.3 2191.65  4840.8 2191.82  4851.4 2191.23
    4860 2188.97  4865.3 2188.56  4883.1  2183.2    4891  2182.3  4896.3 2182.68
  4914.9  2181.5  4936.1 2181.78  4953.1 2181.04  4967.9 2181.16  4978.5 2178.85
  4979.4 2175.42  4979.9 2174.92  4988.2 2174.92  4988.7 2175.42  4989.4 2175.45
  4997.2  2180.4  5002.4  2180.4  5009.9  2184.5  5020.1 2186.61  5025.7 2188.34
  5030.8 2188.22  5040.5  2189.7  5050.7 2192.78  5076.4 2196.19  5101.7 2196.17
#Mann= 3 ,-1 , 0
  4787.8     .07       0  4979.4     .07       0  4988.7     .07       0
Bank Sta=4979.4,4988.7
XS Rating Curve= 0 ,0
Exp/Cntr=0.3,0.1

Type RM Length L Ch R = 1 ,3522    ,440,440,440
BEGIN DESCRIPTION:
Sweetwater Creek Trib 20T2 6.0
END DESCRIPTION:
XS GIS Cut Line= 3
      1383155.02      6830987.98      1383224.76      6830908.42
      1383354.99      6830688.02
#Sta/Elev= 30
  4894.2 2194.44  4922.2 2192.82  4929.8 2191.88  4936.4 2192.04  4958.2 2190.49
  4979.1 2182.28    4997 2179.79  5003.1 2179.79  5008.3 2179.16    5019 2173.91
  5019.5 2173.41  5027.9 2173.41  5028.4 2173.91  5029.7 2175.54  5035.6 2179.03
  5058.6 2180.06  5066.8 2181.14  5072.6 2182.88  5081.8  2184.5  5094.1 2185.63
  5125.4 2186.33  5139.9 2187.29  5152.6 2189.13  5162.4 2188.82  5168.2 2189.19
  5197.9  2192.6  5211.1 2193.62  5232.8 2194.69  5242.4 2194.47    5256 2195.03
#Mann= 3 ,-1 , 0
  4894.2     .07       0    5019     .07       0  5028.4     .07       0
Bank Sta=5019,5028.4
XS Rating Curve= 0 ,0
Exp/Cntr=0.3,0.1

Type RM Length L Ch R = 1 ,3082    ,499,499,499
BEGIN DESCRIPTION:
Sweetwater Creek Trib 20T2 5.0
END DESCRIPTION:
XS GIS Cut Line= 3
      1383554.98      6831238.05      1383607.18      6831094.12
        1383605.      6830938.03
#Sta/Elev= 30
  4846.9 2203.32  4862.3 2201.65  4868.2 2197.86  4878.9 2193.77  4887.6 2191.09
  4892.9 2190.88  4900.1 2189.79  4910.8 2187.58  4918.2 2184.77    4932  2183.3
  4942.7 2184.12  4954.1 2182.22    4964 2183.97  4974.1 2184.39  4979.4 2182.04
  4985.2 2178.23  4995.3  2172.9    5000  2172.9  5001.4  2171.6  5001.9  2171.1
  5010.3  2171.1  5010.8  2171.6  5016.1 2173.83  5026.1 2176.06  5066.1 2178.48
  5076.1 2178.12  5096.1 2180.64  5106.1 2183.79  5126.1 2186.92  5156.1  2188.6
#Mann= 3 ,-1 , 0
  4846.9     .07       0  5001.4     .07       0  5010.8     .07       0
Bank Sta=5001.4,5010.8
XS Rating Curve= 0 ,0
Exp/Cntr=0.3,0.1

Type RM Length L Ch R = 1 ,2583    ,496,496,496
BEGIN DESCRIPTION:
Sweetwater Creek Trib 20T2 4.0
END DESCRIPTION:
XS GIS Cut Line= 3
      1383854.99      6831588.02       1384075.1      6831187.75
      1383705.02      6830388.03
#Sta/Elev= 30
  4543.2 2217.47  4638.4 2206.73  4714.2 2200.91  4748.6 2194.54  4785.2 2190.86
  4801.3 2186.72  4844.9 2185.94  4882.8 2182.27  4910.3 2180.98  4926.3 2178.31
  4954.1 2176.03  5002.6 2175.82  5014.2 2173.93    5017 2172.26  5017.5 2171.76
  5026.5 2172.26  5037.1 2173.09  5043.8 2176.05  5060.1 2177.01  5088.5 2175.66
  5111.4 2176.09  5128.8 2179.84  5134.3    2179    5143 2183.77  5151.7  2184.8
  5363.3 2185.98  5407.4 2188.88  5649.7 2193.71  5752.4  2198.6  5881.2 2206.93
#Mann= 3 ,-1 , 0
  4543.2     .07       0    5017     .07       0  5026.5     .07       0
Bank Sta=5017,5026.5
XS Rating Curve= 0 ,0
Exp/Cntr=0.3,0.1

Type RM Length L Ch R = 1 ,2087    ,498,498,498
BEGIN DESCRIPTION:
Sweetwater Creek Trib 20T2 3.0
END DESCRIPTION:
XS GIS Cut Line= 3
      1384055.03      6831587.99      1384415.52      6831447.78
      1384804.97      6831038.03
#Sta/Elev= 30
  4613.2 2199.09  4615.9 2199.09  4622.8 2197.27  4682.5  2192.7  4688.3 2191.56
  4784.8 2183.65  4881.4 2176.89    4960 2173.54  4984.5 2174.08  4992.1 2168.66
  4992.6 2168.16  5001.9 2168.66  5006.6 2168.94  5013.5 2170.76  5020.7 2174.16
  5077.3 2175.76  5084.2 2176.98  5098.4 2177.87    5134 2178.94  5197.5 2182.37
  5303.5 2181.69    5339  2183.7  5374.2 2183.07  5388.4 2184.49  5395.7 2186.09
  5430.9 2185.04  5473.3 2188.96  5487.5 2188.68    5530 2190.32  5565.3 2194.37
#Mann= 3 ,-1 , 0
  4613.2     .07       0  4992.1     .07       0  5001.9     .07       0
Bank Sta=4992.1,5001.9
XS Rating Curve= 0 ,0
Exp/Cntr=0.3,0.1

Type RM Length L Ch R = 1 ,1589    ,497,497,497
BEGIN DESCRIPTION:
Sweetwater Creek Trib 20T2 2.0
END DESCRIPTION:
XS GIS Cut Line= 3
      1384405.01      6831987.99      1384721.66      6831804.66
      1384800.86      6831670.84
#Sta/Elev= 30
  4634.1 2208.48  4647.7 2207.49  4663.5 2204.29  4706.6 2198.04  4722.3 2193.38
  4728.1  2193.9  4738.1 2190.85  4772.8 2182.83  4781.2 2181.68  4786.9 2183.13
  4802.7 2180.09  4808.5  2181.9  4818.4 2180.11  4824.2    2182    4840 2177.23
  4845.8 2178.55  4853.6    2176  4867.3 2174.76  4957.6 2171.42  4963.4 2169.56
  4964.3 2166.04  4964.8 2165.54  4974.1 2166.04  4979.2 2167.03  4992.3 2171.38
  5036.4 2170.95  5065.8 2172.49  5089.1 2174.23  5094.9 2175.29  5155.5 2177.54
#Mann= 3 ,-1 , 0
  4634.1     .07       0  4964.3     .07       0  4974.1     .07       0
Bank Sta=4964.3,4974.1
XS Rating Curve= 0 ,0
Exp/Cntr=0.3,0.1

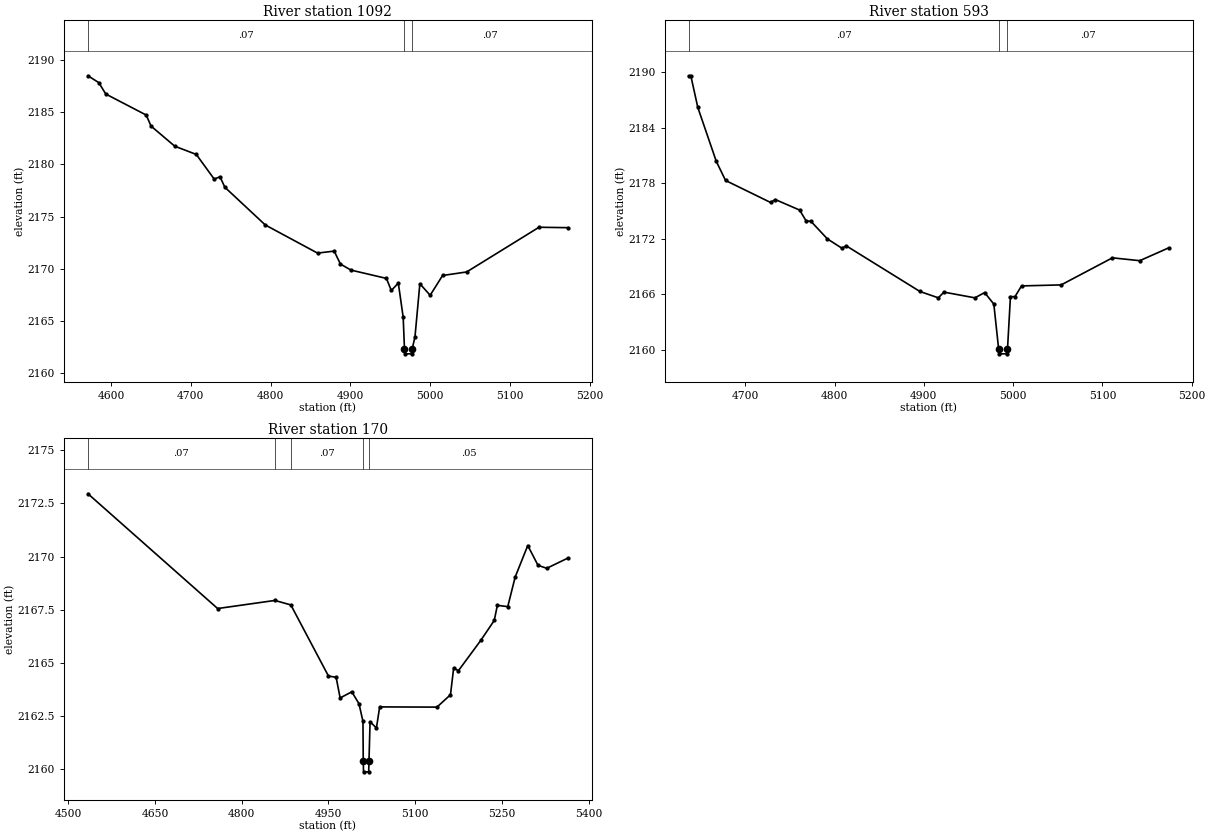
Type RM Length L Ch R = 1 ,1092    ,499,499,499
BEGIN DESCRIPTION:
Sweetwater Creek Trib 20T2 1.0
END DESCRIPTION:
XS GIS Cut Line= 3
      1384754.97      6832288.02      1385107.44      6832043.48
      1385128.21      6831872.03
#Sta/Elev= 30
    4571 2188.51  4584.6 2187.85  4593.3 2186.76    4644 2184.74  4650.1 2183.68
  4679.8 2181.75  4706.8 2180.96  4729.3 2178.59  4736.5 2178.82  4742.6 2177.81
  4793.3 2174.19  4858.8 2171.49  4879.7 2171.68  4887.5 2170.44  4900.7 2169.86
  4945.2 2169.06  4951.3  2167.9  4960.1 2168.61  4966.2 2165.33  4967.8 2162.32
  4968.3 2161.82  4977.1 2161.82  4977.6 2162.32    4981 2163.46  4987.1 2168.55
    5000 2167.44  5015.6 2169.34  5045.8 2169.68  5136.5 2173.97  5172.7 2173.93
#Mann= 3 ,-1 , 0
    4571     .07       0  4967.8     .07       0  4977.6     .07       0
Bank Sta=4967.8,4977.6
XS Rating Curve= 0 ,0
Exp/Cntr=0.3,0.1

Type RM Length L Ch R = 1 ,593     ,423,423,423
BEGIN DESCRIPTION:
Sweetwater Creek Trib 20T2 2461
END DESCRIPTION:
XS GIS Cut Line= 3
      1385405.01      6832487.96      1385499.96      6832137.18
      1385466.91      6831966.35
#Sta/Elev= 30
  4636.6 2189.64  4639.1 2189.64  4646.9 2186.22  4667.6 2180.38    4678 2178.31
  4728.4 2175.93  4733.6 2176.25  4760.9 2175.11  4768.3 2173.92  4773.5  2173.9
    4792 2171.99  4808.1 2170.99  4813.3 2171.23  4895.6  2166.3  4916.3 2165.61
  4922.5 2166.23  4957.2 2165.61  4968.1 2166.18  4978.4 2164.93  4983.8 2160.05
  4984.3 2159.55  4993.2 2159.55  4993.7 2160.05    4997 2165.74  5002.1 2165.74
  5009.4  2166.9  5053.8 2167.01  5111.2 2169.94  5141.8 2169.63    5174 2171.01
#Mann= 3 ,-1 , 0
  4636.6     .07       0  4983.8     .07       0  4993.7     .07       0
Bank Sta=4983.8,4993.7
XS Rating Curve= 0 ,0
Exp/Cntr=0.3,0.1

Type RM Length L Ch R = 1 ,170     ,0,0,0
BEGIN DESCRIPTION:
Sweetwater Creek Trib 20T2 4142
END DESCRIPTION:
XS GIS Cut Line= 3
      1385822.22      6832570.23      1385885.21       6832108.5
      1385551.41      6831962.83
#Sta/Elev= 30
    4534 2172.95  4758.3 2167.56  4857.3 2167.94  4884.9 2167.73    4950 2164.39
  4963.3 2164.33  4970.2 2163.36  4990.4 2163.65  5002.8 2163.09  5009.7 2162.26
  5010.2 2160.39  5010.7 2159.89  5019.6 2159.89  5020.1 2160.39    5022 2162.24
    5033 2161.95  5038.6 2162.94  5137.7 2162.93  5161.1 2163.51  5166.6 2164.77
  5174.8 2164.64  5213.4 2166.06  5236.8    2167  5242.2 2167.71  5260.2 2167.65
    5273 2169.04  5294.8 2170.52  5312.5 2169.59  5327.6 2169.45  5364.2 2169.93
#Mann= 5 ,-1 , 0
    4534     .07       0  4857.3    .035       0  4884.9     .07       0
  5010.2     .05       0  5020.1     .05       0
Bank Sta=5010.2,5020.1
XS Rating Curve= 0 ,0
Exp/Cntr=0.3,0.1

Chan Stop Cuts=-1
Use User Specified Reach Order=0
Composite Channel Slope=5