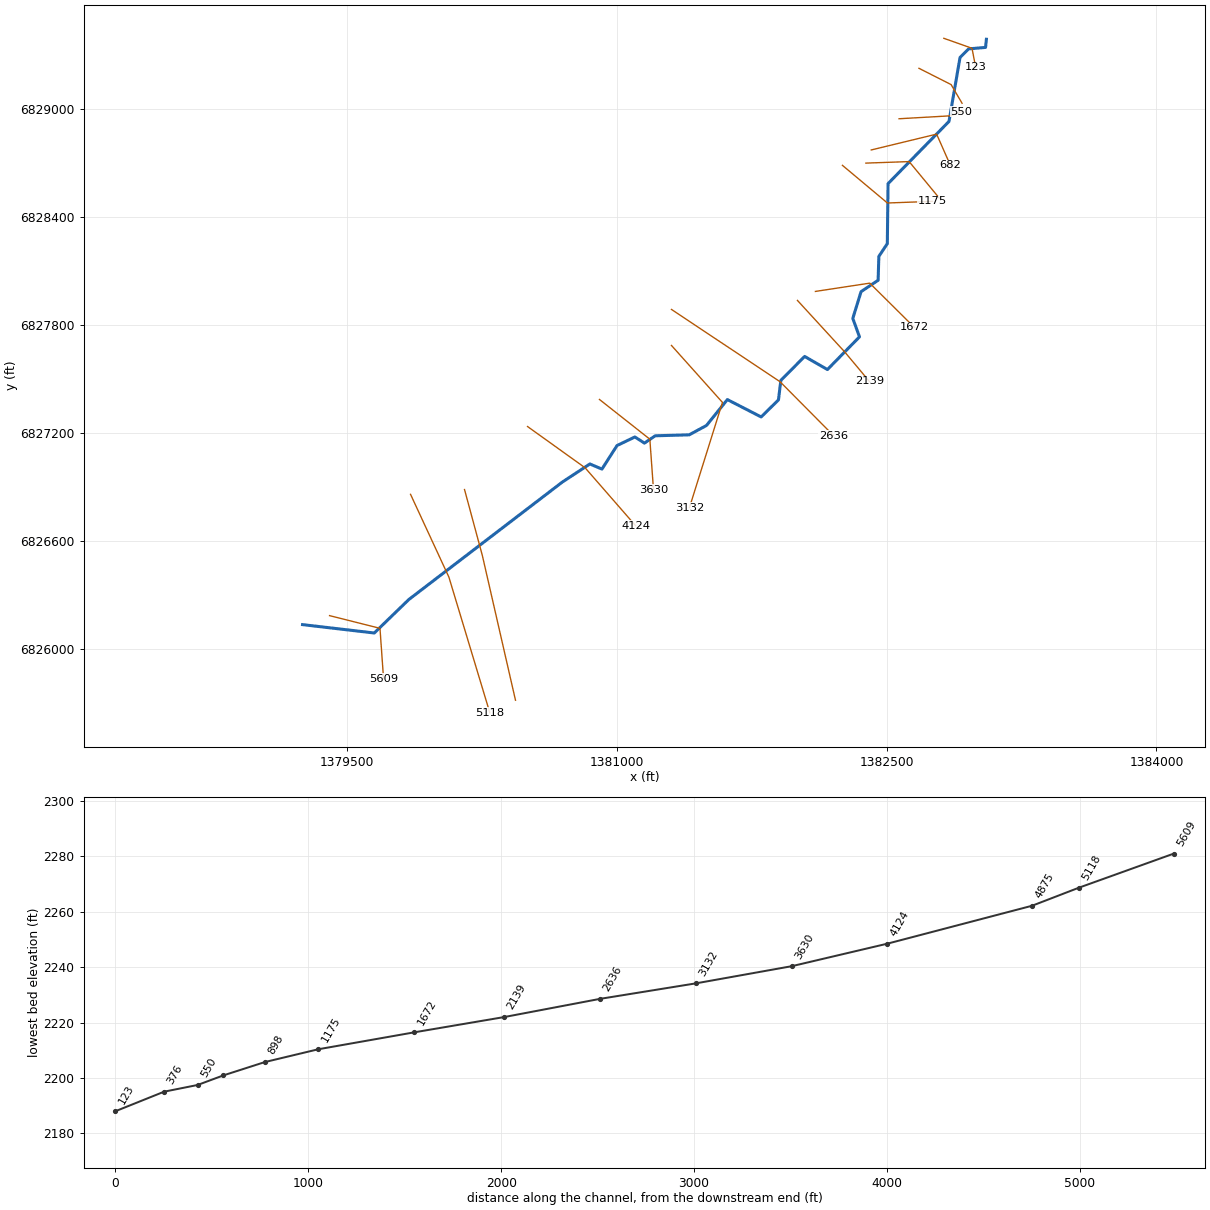
--- Sweetwater Creek Trib 20T2_1.prj (project) ---

Proj Title=Sweetwater Creek Trib 20T2_1 Base Level Engineering
Current Plan=p01
Default Exp/Contr=0.3,0.1
English Units
Geom File=g01
Flow File=f01
Plan File=p01
Y Axis Title=Elevation
X Axis Title(PF)=Main Channel Distance
X Axis Title(XS)=Station
BEGIN DESCRIPTION:
Sweetwater Creek Trib 20T2_1
END DESCRIPTION:
DSS Export Rating Curves= 0
DSS Export Rating Curve Sorted= 0
DSS Export Volume Flow Curves= 0
DXF OffsetX= 0
DXF OffsetY= 0
DXF ScaleX= 1
DXF ScaleY= 10

--- Sweetwater Creek Trib 20T2_1.p01 (plan) ---

Plan Title=Multiple Run
Short Identifier=Multiple
Geom File=g01
Flow File=f01
Subcritical Flow
K Sum by GR= 0
Std Step Tol= 0.01
Critical Tol= 0.01
Num of Std Step Trials= 20
Max Error Tol= 0.3
Flow Tol Ratio= 0.001
Split Flow NTrial= 30
Split Flow Tol= 0.02
Split Flow Ratio= 0.02
Log Output Level= 0
Friction Slope Method= 1
Unsteady Friction Slope Method= 2
Unsteady Bridges Friction Slope Method= 1
Parabolic Critical Depth
Global Vel Dist=  1 , 1 , 1
Global Log Level= 0
CheckData=True
Encroach Param= -1, 0, 0, 0
BEGIN DESCRIPTION:
Multiple Run
END DESCRIPTION:

--- Sweetwater Creek Trib 20T2_1.f01 (steady flow) ---

Flow Title=Multiple
Number of Profiles=7
Profile Names=10-year,25-year,50-year,1pct_min,100-year,1pct_plu,500-year
River Rch & RM= Sweetwater Creek,Reach-1,5609
     171     238     293     180     360     718     547
Boundary for River Rch & Prof#=Sweetwater Creek,Reach-1,1
Up Type=0
Dn Type=3
Dn Slope=0.005
Boundary for River Rch & Prof#=Sweetwater Creek,Reach-1,2
Up Type=0
Dn Type=3
Dn Slope=0.005
Boundary for River Rch & Prof#=Sweetwater Creek,Reach-1,3
Up Type=0
Dn Type=3
Dn Slope=0.005
Boundary for River Rch & Prof#=Sweetwater Creek,Reach-1,4
Up Type=0
Dn Type=3
Dn Slope=0.005
Boundary for River Rch & Prof#=Sweetwater Creek,Reach-1,5
Up Type=0
Dn Type=3
Dn Slope=0.005
Boundary for River Rch & Prof#=Sweetwater Creek,Reach-1,6
Up Type=0
Dn Type=3
Dn Slope=0.005
Boundary for River Rch & Prof#=Sweetwater Creek,Reach-1,7
Up Type=0
Dn Type=3
Dn Slope=0.005

--- Sweetwater Creek Trib 20T2_1.g01 (geometry) ---

Geom Title=Existing Conditions

River Reach=Sweetwater Creek,Reach-1
Reach XY= 30
      1379255.00      6826138.00      1379653.53      6826091.53
      1379845.32      6826277.22      1380698.95      6826929.84
      1380851.68      6827029.98      1380918.68      6827001.51
      1381002.46      6827132.29      1381101.76      6827179.76
      1381154.90      6827145.80      1381214.59      6827186.46
      1381403.48      6827191.74      1381499.39      6827243.59
      1381615.63      6827387.45      1381803.37      6827291.09
      1381899.48      6827385.56      1381912.86      6827494.17
      1382045.00      6827627.04      1382171.67      6827554.20
      1382349.89      6827735.71      1382312.59      6827837.99
      1382358.55      6827986.70      1382453.34      6828049.84
      1382457.39      6828182.46      1382504.48      6828253.22
      1382508.54      6828586.54      1382847.19      6828931.81
      1382908.51      6829286.75      1382956.27      6829334.53
      1383050.32      6829342.75      1383055.00      6829388.00

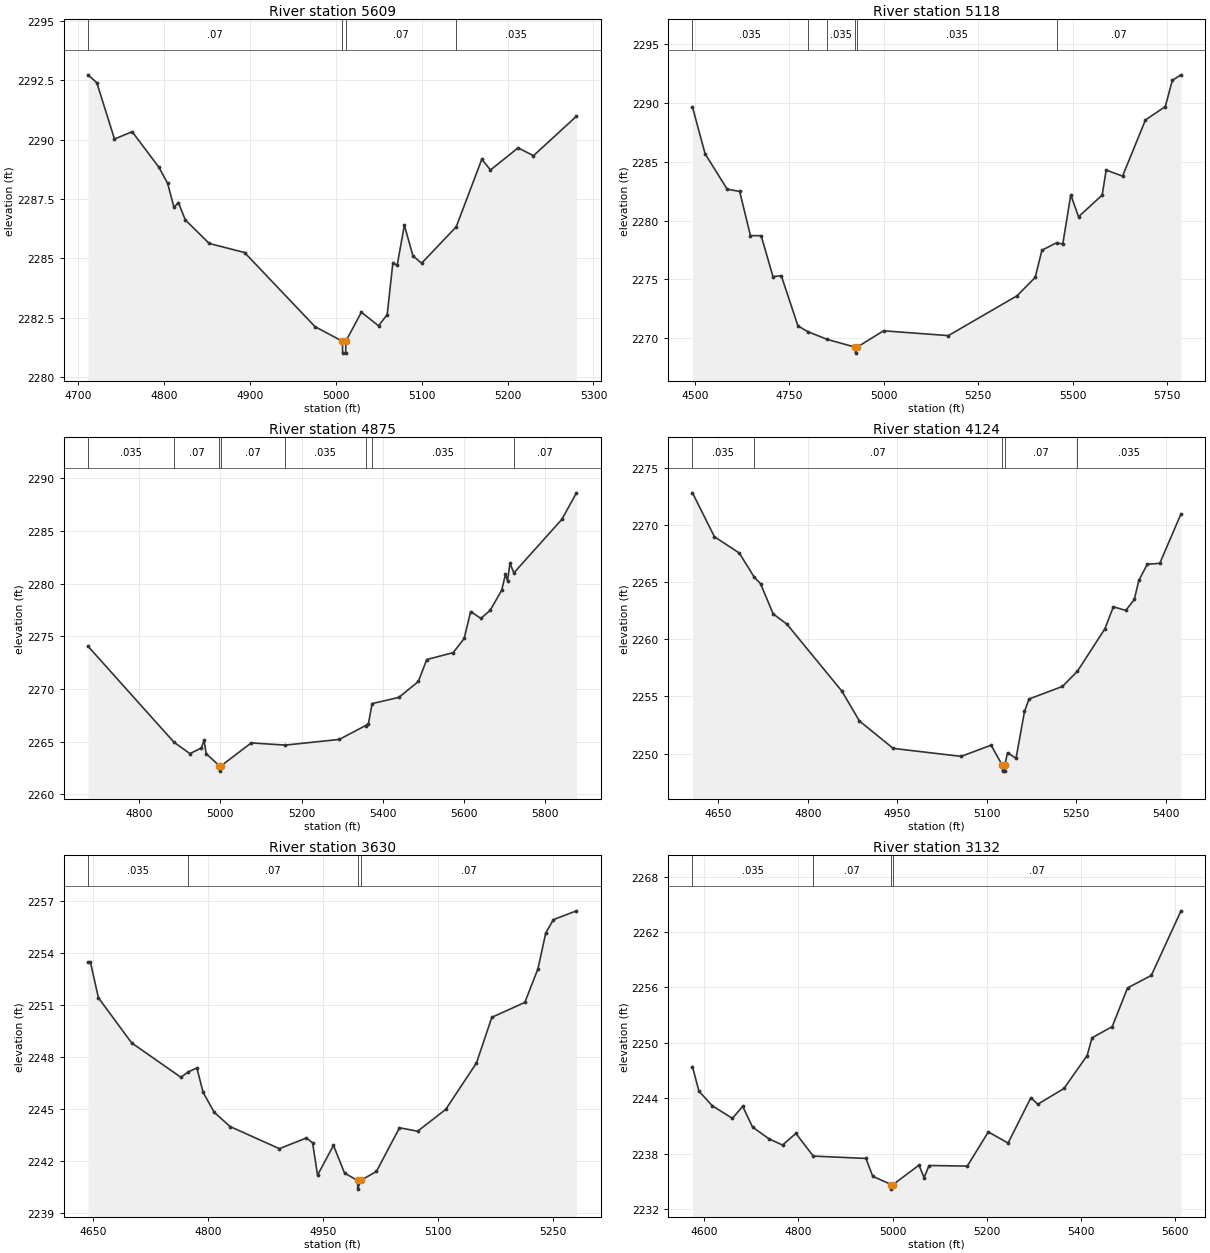
Type RM Length L Ch R = 1,5609,491,491,491
BEGIN DESCRIPTION:
Sweetwater Creek Trib 20T2_1 10.0
END DESCRIPTION:
XS GIS Cut Line= 3
      1379405.03      6826187.99      1379685.20      6826117.51
      1379705.00      6825838.01
#Sta/Elev= 30
  4711.1 2292.72  4721.4 2292.39  4742.0 2290.02  4762.6 2290.33  4793.6 2288.84
  4803.9 2288.16  4811.3 2287.15  4816.4 2287.35  4824.5 2286.62  4852.4 2285.63
  4893.5 2285.25  4975.7 2282.13  5007.5 2281.52  5007.8 2281.02  5011.3 2281.02
  5011.5 2281.52  5029.6 2282.74  5049.6 2282.17  5059.7 2282.64  5066.3 2284.82
  5071.3 2284.71  5079.7 2286.40  5089.7 2285.11  5099.8 2284.80  5140.1 2286.33
  5169.9 2289.17  5180.0 2288.72  5212.2 2289.65  5230.1 2289.32  5280.2 2290.98
#Mann=4,-1,0
  4711.1    0.07       0  5007.5    0.07       0  5011.5    0.07       0
  5140.1   0.035       0
Bank Sta=5007.5,5011.5
Exp/Cntr=0.3,0.1

Type RM Length L Ch R = 1,5118,243,243,243
BEGIN DESCRIPTION:
Sweetwater Creek Trib 20T2_1 9.0
END DESCRIPTION:
XS GIS Cut Line= 3
      1379855.00      6826861.40      1380068.21      6826401.63
      1380295.82      6825648.27
#Sta/Elev= 30
  4493.2 2289.66  4526.7 2285.68  4585.1 2282.67  4618.2 2282.48  4646.7 2278.72
  4675.2 2278.71  4706.4 2275.23  4728.4 2275.31  4772.5 2271.04  4798.9 2270.54
  4850.1 2269.89  4924.8 2269.22  4925.1 2268.72  4928.8 2269.22  4999.2 2270.62
  5170.9 2270.21  5352.8 2273.60  5400.8 2275.16  5418.8 2277.48  5457.5 2278.11
  5473.9 2278.00  5495.1 2282.19  5515.7 2280.32  5578.3 2282.17  5588.8 2284.30
  5632.2 2283.78  5692.9 2288.56  5745.5 2289.70  5764.0 2291.93  5787.0 2292.40
#Mann=6,-1,0
  4493.2   0.035       0  4798.9    0.07       0  4850.1   0.035       0
  4924.8   0.035       0  4928.8   0.035       0  5457.5    0.07       0
Bank Sta=4924.8,4928.8
Exp/Cntr=0.3,0.1

Type RM Length L Ch R = 1,4875,751,751,751
BEGIN DESCRIPTION:
Sweetwater Creek Trib 20T2_1 8.0
END DESCRIPTION:
XS GIS Cut Line= 3
      1380155.01      6826887.97      1380253.95      6826522.17
      1380438.18      6825718.35
#Sta/Elev= 30
  4673.7 2274.05  4885.5 2264.94  4925.0 2263.85  4953.4 2264.40  4959.7 2265.15
  4964.9 2263.85  4997.6 2262.69  4997.9 2262.19  5001.6 2262.69  5076.0 2264.87
  5159.6 2264.66  5292.9 2265.20  5357.9 2266.52  5364.7 2266.69  5373.7 2268.60
  5439.7 2269.19  5487.8 2270.70  5508.3 2272.78  5573.6 2273.44  5600.7 2274.79
  5616.5 2277.34  5641.7 2276.69  5664.5 2277.45  5693.0 2279.36  5702.3 2280.87
  5707.4 2280.27  5713.5 2281.92  5723.0 2281.01  5841.2 2286.09  5877.3 2288.61
#Mann=8,-1,0
  4673.7   0.035       0  4885.5    0.07       0  4997.6    0.07       0
  5001.6    0.07       0  5159.6   0.035       0  5357.9    0.07       0
  5373.7   0.035       0  5723.0    0.07       0
Bank Sta=4997.6,5001.6
Exp/Cntr=0.3,0.1

Type RM Length L Ch R = 1,4124,494,494,494
BEGIN DESCRIPTION:
Sweetwater Creek Trib 20T2_1 7.0
END DESCRIPTION:
XS GIS Cut Line= 3
      1380505.02      6827237.98      1380825.03      6827008.82
      1381105.00      6826688.00
#Sta/Elev= 30
  4606.4 2272.82  4643.2 2268.98  4685.0 2267.55  4710.0 2265.44  4720.6 2264.87
  4741.7 2262.23  4764.8 2261.33  4857.0 2255.47  4886.4 2252.86  4943.0 2250.46
  5057.0 2249.76  5107.3 2250.74  5126.2 2248.97  5126.5 2248.47  5130.0 2248.47
  5130.2 2248.97  5134.8 2250.08  5149.1 2249.59  5163.3 2253.69  5170.9 2254.78
  5226.9 2255.88  5252.0 2257.20  5298.1 2260.92  5312.4 2262.85  5333.2 2262.53
  5347.5 2263.49  5355.1 2265.16  5369.3 2266.57  5390.2 2266.65  5425.8 2270.98
#Mann=5,-1,0
  4606.4   0.035       0  4710.0    0.07       0  5126.2    0.07       0
  5130.2    0.07       0  5252.0   0.035       0
Bank Sta=5126.2,5130.2
Exp/Cntr=0.3,0.1

Type RM Length L Ch R = 1,3630,498,498,498
BEGIN DESCRIPTION:
Sweetwater Creek Trib 20T2_1 6.0
END DESCRIPTION:
XS GIS Cut Line= 3
      1380904.98      6827388.02      1381184.84      6827167.50
      1381205.00      6826888.02
#Sta/Elev= 30
  4643.7 2253.50  4646.9 2253.50  4657.3 2251.43  4700.6 2248.82  4764.8 2246.83
  4774.0 2247.13  4785.6 2247.37  4793.7 2245.96  4808.1 2244.81  4828.9 2243.98
  4893.1 2242.70  4928.3 2243.32  4936.4 2243.04  4942.8 2241.17  4963.6 2242.89
  4978.0 2241.29  4994.9 2240.86  4995.2 2240.36  4998.9 2240.86  5019.5 2241.38
  5049.6 2243.91  5073.2 2243.71  5109.8 2244.97  5149.9 2247.66  5169.9 2250.30
  5212.9 2251.16  5230.1 2253.12  5240.1 2255.17  5250.1 2255.95  5280.2 2256.46
#Mann=4,-1,0
  4643.7   0.035       0  4774.0    0.07       0  4994.9    0.07       0
  4998.9    0.07       0
Bank Sta=4994.9,4998.9
Exp/Cntr=0.3,0.1

Type RM Length L Ch R = 1,3132,496,496,496
BEGIN DESCRIPTION:
Sweetwater Creek Trib 20T2_1 5.0
END DESCRIPTION:
XS GIS Cut Line= 3
      1381305.03      6827687.97      1381588.30      6827371.80
      1381405.00      6826788.00
#Sta/Elev= 30
  4575.5 2247.41  4589.3 2244.76  4617.7 2243.17  4660.3 2241.81  4682.0 2243.12
  4702.9 2240.87  4738.0 2239.59  4766.5 2238.92  4794.9 2240.18  4831.8 2237.72
  4943.6 2237.47  4957.9 2235.53  4997.2 2234.64  4997.4 2234.14  5001.2 2234.64
  5056.1 2236.74  5066.9 2235.39  5077.4 2236.70  5158.6 2236.64  5203.1 2240.34
  5245.1 2239.14  5293.5 2244.06  5307.9 2243.34  5363.6 2245.05  5412.8 2248.62
  5423.1 2250.54  5466.0 2251.76  5498.5 2255.95  5549.0 2257.31  5611.9 2264.31
#Mann=4,-1,0
  4575.5   0.035       0  4831.8    0.07       0  4997.2    0.07       0
  5001.2    0.07       0
Bank Sta=4997.2,5001.2
Exp/Cntr=0.3,0.1

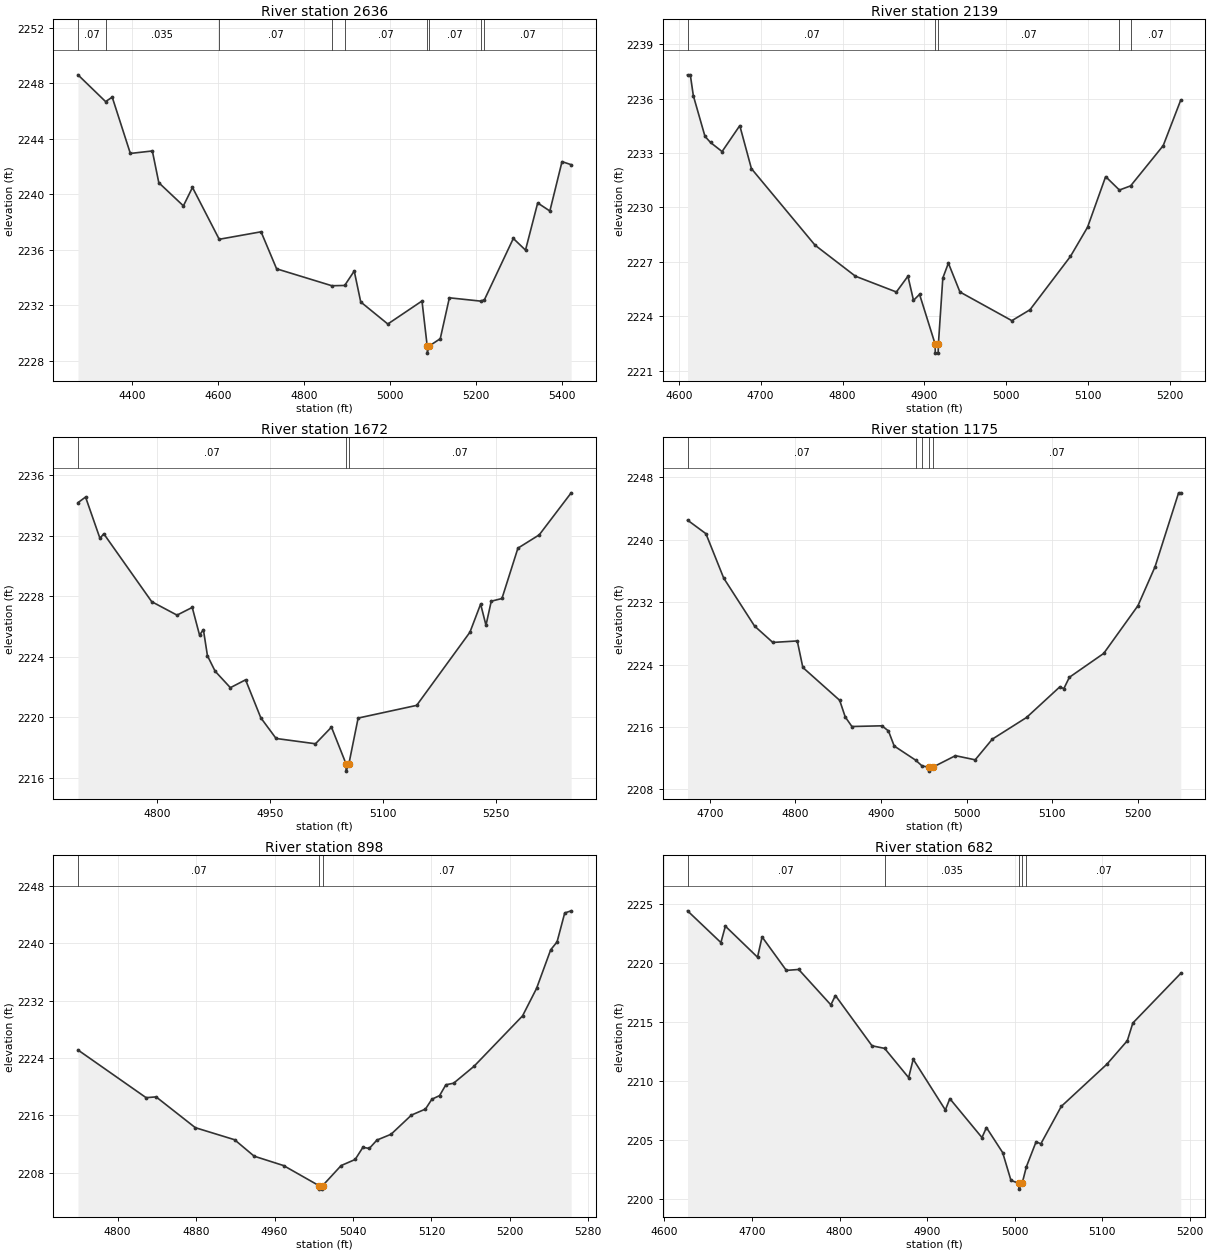
Type RM Length L Ch R = 1,2636,497,497,497
BEGIN DESCRIPTION:
Sweetwater Creek Trib 20T2_1 4.0
END DESCRIPTION:
XS GIS Cut Line= 3
      1381305.04      6827887.97      1381908.61      6827486.50
      1382205.03      6827187.97
#Sta/Elev= 30
  4275.1 2248.62  4339.3 2246.69  4354.7 2247.01  4396.8 2242.95  4447.9 2243.13
  4462.9 2240.84  4520.0 2239.17  4541.1 2240.50  4603.2 2236.76  4700.4 2237.30
  4736.5 2234.63  4864.8 2233.41  4894.6 2233.43  4916.8 2234.47  4931.9 2232.24
  4994.8 2230.65  5074.2 2232.31  5086.3 2229.05  5086.6 2228.55  5090.3 2229.05
  5116.6 2229.59  5137.8 2232.54  5210.7 2232.30  5219.2 2232.40  5286.3 2236.82
  5314.6 2235.98  5342.9 2239.38  5371.2 2238.80  5399.4 2242.36  5420.7 2242.14
#Mann=9,-1,0
  4275.1    0.07       0  4339.3   0.035       0  4603.2    0.07       0
  4864.8   0.035       0  4894.6    0.07       0  5086.3    0.07       0
  5090.3    0.07       0  5210.7   0.035       0  5219.2    0.07       0
Bank Sta=5086.3,5090.3
Exp/Cntr=0.3,0.1

Type RM Length L Ch R = 1,2139,467,467,467
BEGIN DESCRIPTION:
Sweetwater Creek Trib 20T2_1 3.0
END DESCRIPTION:
XS GIS Cut Line= 3
      1382005.00      6827938.00      1382268.37      6827651.31
      1382404.98      6827488.02
#Sta/Elev= 30
  4610.7 2237.31  4614.1 2237.31  4617.8 2236.16  4632.0 2233.92  4638.8 2233.58
  4652.9 2233.08  4674.5 2234.51  4688.7 2232.14  4766.4 2227.92  4815.7 2226.21
  4865.7 2225.34  4879.8 2226.21  4886.6 2224.88  4894.0 2225.21  4913.0 2222.47
  4913.2 2221.97  4916.7 2221.97  4917.0 2222.47  4922.4 2226.11  4929.2 2226.93
  4943.3 2225.34  5006.7 2223.76  5028.8 2224.36  5078.2 2227.30  5099.1 2228.91
  5121.2 2231.70  5138.0 2230.96  5151.7 2231.19  5191.5 2233.41  5212.9 2235.92
#Mann=5,-1,0
  4610.7    0.07       0  4913.0    0.07       0  4917.0    0.07       0
  5138.0   0.035       0  5151.7    0.07       0
Bank Sta=4913,4917
Exp/Cntr=0.3,0.1

Type RM Length L Ch R = 1,1672,497,497,497
BEGIN DESCRIPTION:
Sweetwater Creek Trib 20T2_1 2.0
END DESCRIPTION:
XS GIS Cut Line= 3
      1382105.02      6827988.00      1382406.84      6828033.94
      1382655.01      6827787.99
#Sta/Elev= 30
  4694.7 2234.20  4704.8 2234.57  4723.9 2231.84  4729.0 2232.14  4792.6 2227.65
  4826.2 2226.76  4846.4 2227.27  4856.1 2225.44  4861.2 2225.80  4866.6 2224.07
  4876.8 2223.05  4897.0 2221.96  4917.2 2222.48  4937.4 2219.97  4957.7 2218.60
  5010.0 2218.25  5031.2 2219.35  5050.4 2216.94  5050.7 2216.44  5054.4 2216.94
  5066.6 2219.95  5144.3 2220.79  5215.0 2225.63  5229.2 2227.49  5236.3 2226.09
  5243.3 2227.68  5257.5 2227.86  5278.7 2231.19  5307.0 2232.07  5349.4 2234.85
#Mann=3,-1,0
  4694.7    0.07       0  5050.4    0.07       0  5054.4    0.07       0
Bank Sta=5050.4,5054.4
Exp/Cntr=0.3,0.1

Type RM Length L Ch R = 1,1175,277,277,277
BEGIN DESCRIPTION:
Sweetwater Creek Trib 20T2_1 1.0
END DESCRIPTION:
XS GIS Cut Line= 3
      1382254.97      6828688.03      1382504.95      6828478.93
      1382754.98      6828488.00
#Sta/Elev= 30
  4674.1 2242.51  4695.6 2240.77  4716.4 2235.07  4752.4 2228.93  4773.7 2226.83
  4802.3 2227.02  4808.8 2223.62  4851.8 2219.41  4858.3 2217.28  4866.1 2216.05
  4901.2 2216.14  4908.8 2215.48  4915.5 2213.55  4940.5 2211.74  4948.1 2210.99
  4956.5 2210.83  4956.7 2210.33  4960.5 2210.83  4987.0 2212.31  5010.1 2211.78
  5030.1 2214.43  5070.1 2217.21  5108.7 2221.11  5113.7 2220.92  5120.1 2222.36
  5160.2 2225.42  5200.2 2231.54  5220.2 2236.54  5247.7 2246.01  5250.2 2246.01
#Mann=5,-1,0
  4674.1    0.07       0  4940.5   0.035       0  4948.1    0.07       0
  4956.5    0.07       0  4960.5    0.07       0
Bank Sta=4956.5,4960.5
Exp/Cntr=0.3,0.1

Type RM Length L Ch R = 1,898,216,216,216
BEGIN DESCRIPTION:
Sweetwater Creek Trib 20T2_1 4179
END DESCRIPTION:
XS GIS Cut Line= 3
      1382385.38      6828700.42      1382625.73      6828708.76
      1382792.94      6828506.40
#Sta/Elev= 30
  4759.5 2225.13  4829.0 2218.47  4839.2 2218.58  4879.2 2214.28  4919.2 2212.60
  4939.2 2210.30  4969.2 2208.99  5005.1 2206.20  5005.3 2205.70  5008.8 2205.70
  5009.1 2206.20  5027.9 2208.99  5042.2 2209.84  5050.1 2211.54  5056.6 2211.38
  5064.4 2212.55  5078.8 2213.36  5099.6 2216.04  5113.9 2216.88  5120.4 2218.25
  5128.3 2218.76  5134.7 2220.27  5142.6 2220.49  5163.4 2222.85  5212.9 2229.89
  5227.2 2233.73  5241.6 2239.12  5248.1 2240.22  5255.9 2244.26  5262.5 2244.56
#Mann=3,-1,0
  4759.5    0.07       0  5005.1    0.07       0  5009.1    0.07       0
Bank Sta=5005.1,5009.1
Exp/Cntr=0.3,0.1

Type RM Length L Ch R = 1,682,132,132,132
BEGIN DESCRIPTION:
Sweetwater Creek Trib 20T2_1 2552
END DESCRIPTION:
XS GIS Cut Line= 3
      1382415.37      6828773.46      1382778.39      6828861.31
      1382855.00      6828687.99
#Sta/Elev= 30
  4626.5 2224.45  4664.6 2221.76  4669.7 2223.15  4706.4 2220.52  4711.6 2222.24
  4739.3 2219.40  4753.4 2219.48  4790.1 2216.48  4795.3 2217.27  4837.1 2213.01
  4851.5 2212.79  4878.9 2210.31  4884.1 2211.87  4920.8 2207.57  4925.9 2208.53
  4962.6 2205.23  4967.7 2206.08  4986.2 2203.96  4995.7 2201.60  5004.5 2201.36
  5004.8 2200.86  5008.5 2201.36  5013.3 2202.76  5024.4 2204.88  5029.8 2204.70
  5053.1 2207.87  5105.2 2211.45  5128.5 2213.44  5134.8 2214.94  5189.5 2219.15
#Mann=5,-1,0
  4626.5    0.07       0  4851.5   0.035       0  5004.5   0.035       0
  5008.5   0.035       0  5013.3    0.07       0
Bank Sta=5004.5,5008.5
Exp/Cntr=0.3,0.1

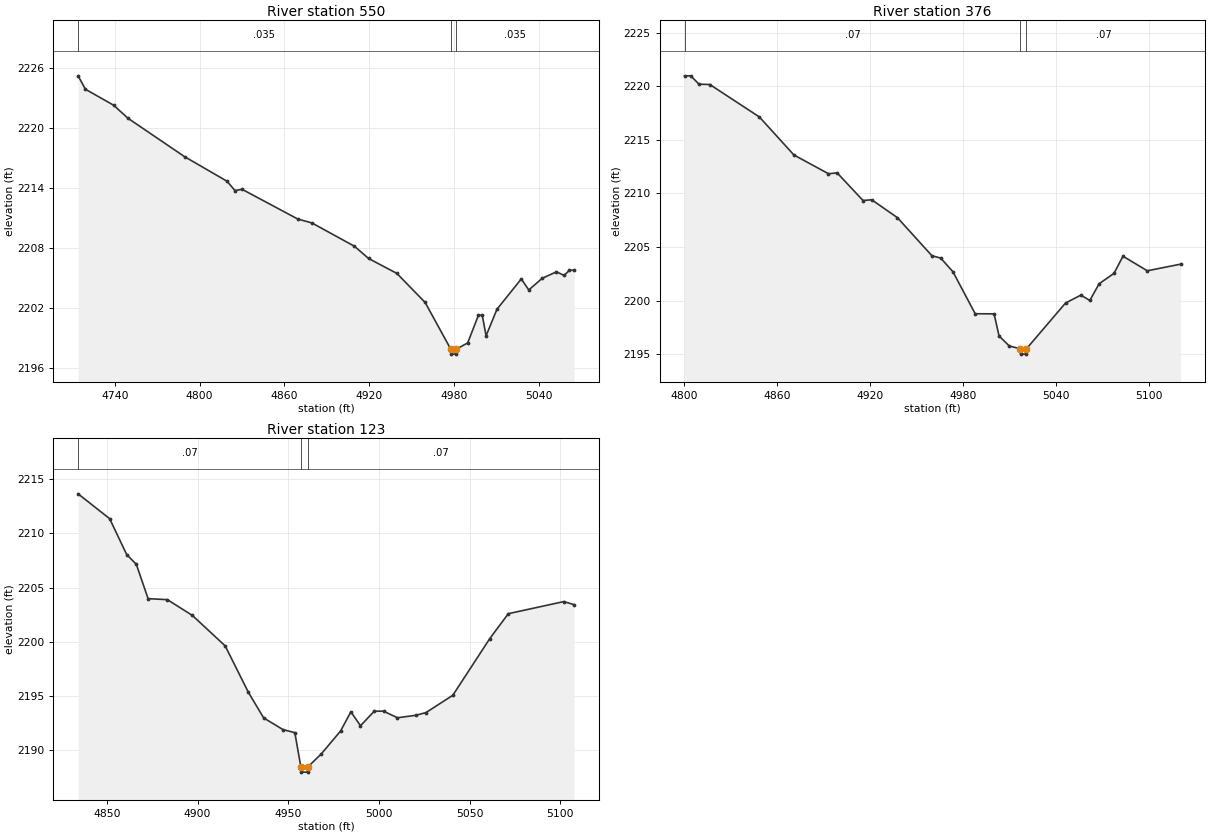
Type RM Length L Ch R = 1,550,174,174,174
BEGIN DESCRIPTION:
Sweetwater Creek Trib 20T2_1 4178
END DESCRIPTION:
XS GIS Cut Line= 3
      1382569.85      6828946.66      1382855.29      6828962.88
      1382916.15      6828985.71
#Sta/Elev= 30
  4714.1 2225.22  4719.3 2223.88  4739.3 2222.28  4749.3 2220.99  4789.4 2217.15
  4819.4 2214.70  4825.1 2213.76  4830.1 2213.89  4869.5 2210.92  4879.5 2210.53
  4909.6 2208.20  4919.6 2206.98  4939.6 2205.49  4959.6 2202.59  4977.7 2197.93
  4977.9 2197.43  4981.4 2197.43  4981.7 2197.93  4989.7 2198.55  4997.3 2201.31
  5000.0 2201.31  5002.7 2199.26  5010.4 2201.91  5027.6 2204.94  5032.9 2203.84
  5042.4 2205.00  5052.5 2205.65  5057.9 2205.29  5061.7 2205.81  5065.0 2205.81
#Mann=3,-1,0
  4714.1   0.035       0  4977.7   0.035       0  4981.7   0.035       0
Bank Sta=4977.7,4981.7
Exp/Cntr=0.3,0.1

Type RM Length L Ch R = 1,376,253,253,253
BEGIN DESCRIPTION:
Sweetwater Creek Trib 20T2_1 4177
END DESCRIPTION:
XS GIS Cut Line= 3
      1382680.49      6829226.62      1382858.78      6829136.43
      1382919.83      6829032.66
#Sta/Elev= 30
  4800.2 2220.98  4804.2 2220.98  4809.5 2220.20  4816.5 2220.17  4848.5 2217.14
  4870.8 2213.59  4893.1 2211.84  4898.7 2211.92  4915.4 2209.34  4921.0 2209.41
  4937.6 2207.74  4959.9 2204.18  4965.5 2203.97  4973.4 2202.70  4987.8 2198.77
  5000.0 2198.76  5003.2 2196.70  5009.8 2195.76  5016.9 2195.50  5017.1 2195.00
  5020.6 2195.00  5020.9 2195.50  5046.1 2199.77  5056.0 2200.51  5061.8 2200.01
  5067.8 2201.57  5077.4 2202.54  5083.2 2204.14  5098.9 2202.78  5120.4 2203.40
#Mann=3,-1,0
  4800.2    0.07       0  5016.9    0.07       0  5020.9    0.07       0
Bank Sta=5016.9,5020.9
Exp/Cntr=0.3,0.1

Type RM Length L Ch R = 1,123,0,0,0
BEGIN DESCRIPTION:
Sweetwater Creek Trib 20T2_1 4176
END DESCRIPTION:
XS GIS Cut Line= 3
      1382818.57      6829393.26      1382975.00      6829338.00
      1382995.51      6829232.38
#Sta/Elev= 30
  4834.1 2213.67  4851.5 2211.37  4860.9 2208.05  4866.2 2207.15  4872.7 2203.97
  4883.3 2203.88  4897.1 2202.42  4915.2 2199.60  4928.0 2195.30  4936.4 2192.94
  4947.0 2191.86  4953.6 2191.57  4956.9 2188.42  4957.2 2187.92  4960.7 2187.92
  4960.9 2188.42  4968.2 2189.61  4978.8 2191.72  4984.5 2193.50  4989.8 2192.21
  4997.4 2193.56  5002.5 2193.56  5010.2 2192.95  5020.4 2193.18  5025.9 2193.43
  5040.7 2195.03  5061.1 2200.28  5071.3 2202.58  5101.9 2203.70  5107.6 2203.41
#Mann=3,-1,0
  4834.1    0.07       0  4956.9    0.07       0  4960.9    0.07       0
Bank Sta=4956.9,4960.9
Exp/Cntr=0.3,0.1

Chan Stop Cuts=-1