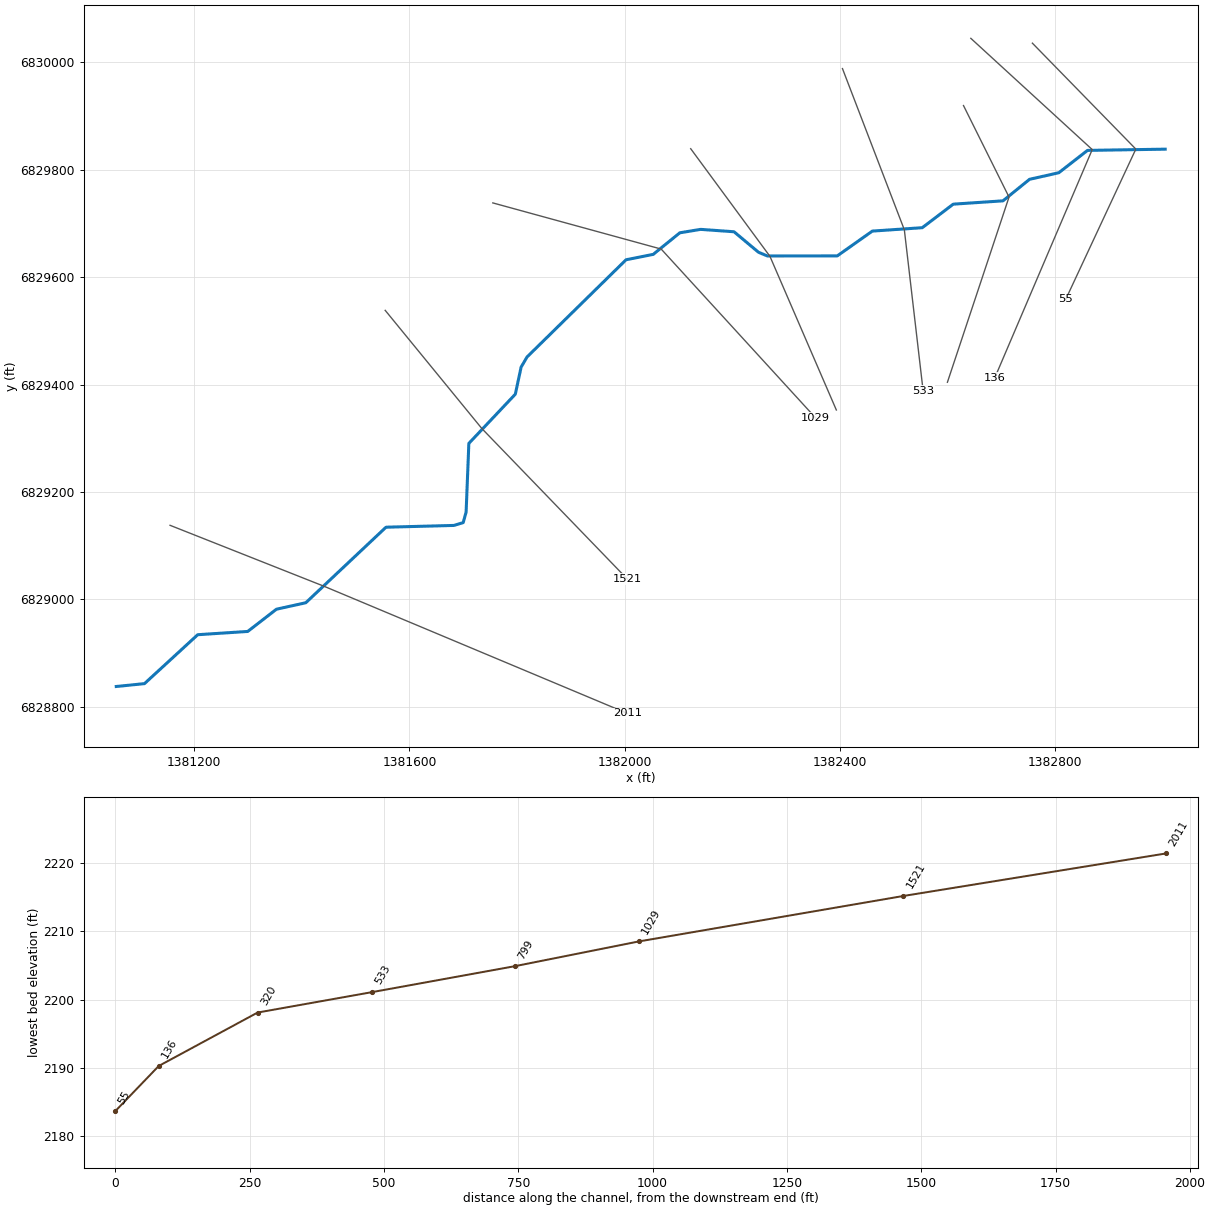
--- Sweetwater Creek Trib 20T2_2.prj (project) ---

Proj Title=Sweetwater Creek Trib 20T2_2 Base Level Engineering
Current Plan=p01
Default Exp/Contr=0.3,0.1
English Units
Geom File=g01
Flow File=f01
Plan File=p01
BEGIN DESCRIPTION:
Sweetwater Creek Trib 20T2_2
END DESCRIPTION:

--- Sweetwater Creek Trib 20T2_2.p01 (plan) ---

Plan Title=Multiple Run
Short Identifier=Multiple
Geom File=g01
Flow File=f01
Subcritical Flow
K Sum by GR= 0
Std Step Tol= 0.01
Critical Tol= 0.01
Num of Std Step Trials= 20
Max Error Tol= 0.3
Flow Tol Ratio= 0.001
Split Flow NTrial= 30
Split Flow Tol= 0.02
Split Flow Ratio= 0.02
Log Output Level= 0
Friction Slope Method= 1
Unsteady Friction Slope Method= 2
Unsteady Bridges Friction Slope Method= 1
Parabolic Critical Depth
Global Vel Dist=  1 , 1 , 1
Global Log Level= 0
CheckData=True
Encroach Param= -1, 0, 0, 0
BEGIN DESCRIPTION:
Multiple Run
END DESCRIPTION:

--- Sweetwater Creek Trib 20T2_2.f01 (steady flow) ---

Flow Title=Multiple
Number of Profiles=7
Profile Names=10-year,25-year,50-year,1pct_min,100-year,1pct_plu,500-year
River Rch & RM= Sweetwater Creek,Reach-1,2011
     133     182     221     135     268     536     400
River Rch & RM= Sweetwater Creek,Reach-1,55
     668    1003    1300     837    1670    3333    2795
Boundary for River Rch & Prof#=Sweetwater Creek,Reach-1,1
Up Type=0
Dn Type=3
Dn Slope=0.005
Boundary for River Rch & Prof#=Sweetwater Creek,Reach-1,2
Up Type=0
Dn Type=3
Dn Slope=0.005
Boundary for River Rch & Prof#=Sweetwater Creek,Reach-1,3
Up Type=0
Dn Type=3
Dn Slope=0.005
Boundary for River Rch & Prof#=Sweetwater Creek,Reach-1,4
Up Type=0
Dn Type=3
Dn Slope=0.005
Boundary for River Rch & Prof#=Sweetwater Creek,Reach-1,5
Up Type=0
Dn Type=3
Dn Slope=0.005
Boundary for River Rch & Prof#=Sweetwater Creek,Reach-1,6
Up Type=0
Dn Type=3
Dn Slope=0.005
Boundary for River Rch & Prof#=Sweetwater Creek,Reach-1,7
Up Type=0
Dn Type=3
Dn Slope=0.005

--- Sweetwater Creek Trib 20T2_2.g01 (geometry) ---

Geom Title=Existing Conditions

River Reach=Sweetwater Creek,Reach-1
Reach XY= 30
      1381055.00      6828838.00      1381107.51      6828843.33
      1381206.50      6828934.39      1381299.44      6828940.45
      1381352.83      6828981.86      1381407.30      6828993.83
      1381556.48      6829134.45      1381682.54      6829137.74
      1381699.99      6829143.01      1381705.39      6829162.59
      1381710.48      6829290.44      1381796.82      6829381.96
      1381807.64      6829432.36      1381818.63      6829451.21
      1382002.70      6829632.17      1382053.25      6829642.22
      1382102.68      6829682.35      1382141.30      6829688.74
      1382203.40      6829684.30      1382248.94      6829646.14
      1382265.51      6829639.21      1382395.33      6829639.37
      1382460.57      6829685.53      1382553.40      6829691.85
      1382610.97      6829735.65      1382703.42      6829741.83
      1382752.82      6829781.89      1382807.18      6829794.11
      1382860.50      6829835.69      1383005.00      6829838.00

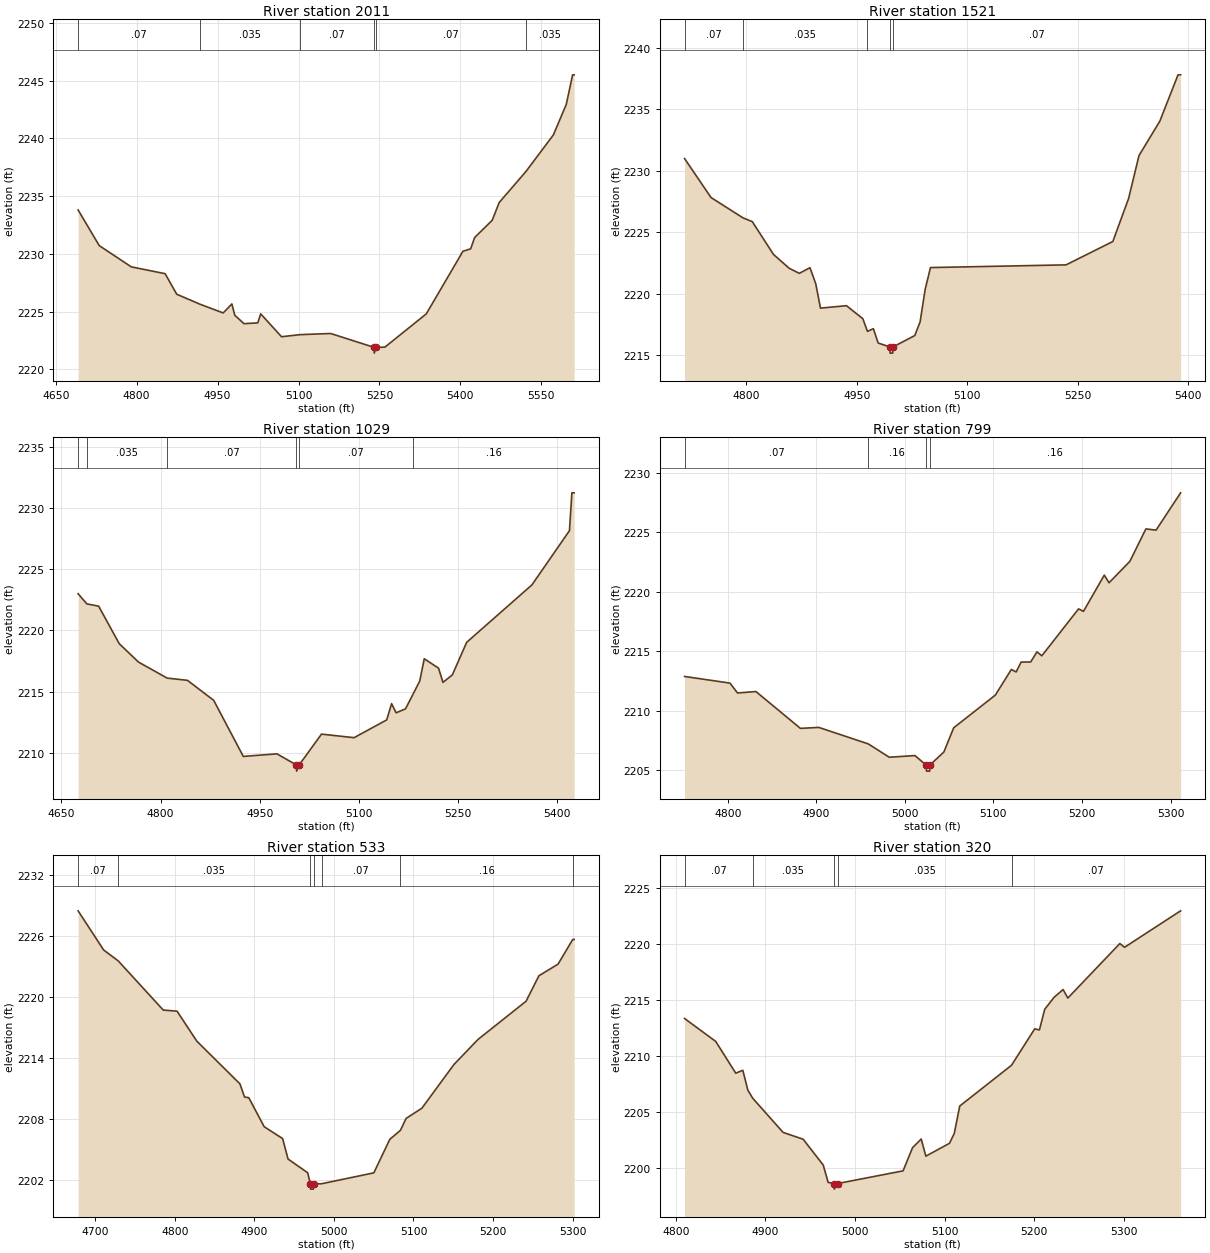
Type RM Length L Ch R = 1,2011,490,490,490
BEGIN DESCRIPTION:
Sweetwater Creek Trib 20T2_2 3.0
END DESCRIPTION:
XS GIS Cut Line= 3
      1381155.02      6829137.99      1381441.81      6829024.32
      1382005.04      6828787.98
#Sta/Elev= 30
  4691.5 2233.80  4730.7 2230.71  4790.1 2228.87  4852.8 2228.28  4874.3 2226.50
  4917.2 2225.64  4960.4 2224.88  4976.5 2225.66  4981.9 2224.68  4999.0 2223.95
  5024.5 2224.02  5029.9 2224.80  5068.5 2222.82  5103.0 2223.00  5159.6 2223.10
  5240.0 2221.90  5240.3 2221.40  5244.0 2221.90  5260.1 2221.92  5336.8 2224.80
  5404.7 2230.22  5419.0 2230.43  5426.4 2231.41  5458.9 2232.90  5471.9 2234.44
  5521.5 2237.13  5572.4 2240.30  5596.2 2242.94  5608.0 2245.50  5610.8 2245.50
#Mann=6,-1,0
  4691.5    0.07       0  4917.2   0.035       0  5103.0    0.07       0
  5240.0   0.035       0  5244.0    0.07       0  5521.5   0.035       0
Bank Sta=5240,5244
Exp/Cntr=0.3,0.1

Type RM Length L Ch R = 1,1521,492,492,492
BEGIN DESCRIPTION:
Sweetwater Creek Trib 20T2_2 2.0
END DESCRIPTION:
XS GIS Cut Line= 3
      1381554.97      6829538.03      1381734.58      6829318.17
      1382005.01      6829037.99
#Sta/Elev= 30
  4716.1 2230.99  4752.0 2227.82  4795.5 2226.16  4808.0 2225.86  4836.8 2223.19
  4858.2 2222.06  4871.9 2221.65  4886.3 2222.11  4894.2 2220.80  4900.6 2218.82
  4935.8 2219.02  4958.1 2217.96  4964.3 2216.93  4972.4 2217.15  4978.9 2215.98
  4994.9 2215.66  4995.1 2215.16  4998.6 2215.16  4998.9 2215.66  5028.6 2216.59
  5035.8 2217.70  5042.7 2220.35  5049.9 2222.12  5233.9 2222.34  5297.4 2224.24
  5318.8 2227.74  5332.9 2231.23  5361.2 2234.03  5385.9 2237.80  5389.4 2237.80
#Mann=5,-1,0
  4716.1    0.07       0  4795.5   0.035       0  4964.3    0.07       0
  4994.9    0.07       0  4998.9    0.07       0
Bank Sta=4994.9,4998.9
Exp/Cntr=0.3,0.1

Type RM Length L Ch R = 1,1029,230,230,230
BEGIN DESCRIPTION:
Sweetwater Creek Trib 20T2_2 1.0
END DESCRIPTION:
XS GIS Cut Line= 3
      1381755.02      6829737.99      1382068.04      6829652.06
      1382354.99      6829338.01
#Sta/Elev= 30
  4675.4 2222.99  4688.6 2222.16  4706.5 2221.97  4737.6 2218.91  4766.7 2217.41
  4810.1 2216.10  4840.7 2215.92  4880.4 2214.29  4925.2 2209.71  4976.1 2209.92
  5005.6 2209.01  5005.8 2208.51  5009.6 2209.01  5043.4 2211.53  5092.7 2211.24
  5142.0 2212.69  5149.4 2214.02  5156.2 2213.27  5170.4 2213.59  5181.4 2214.74
  5192.0 2215.87  5198.8 2217.68  5220.4 2216.91  5227.1 2215.75  5241.3 2216.37
  5262.9 2219.02  5361.6 2223.71  5418.3 2228.13  5422.0 2231.22  5425.4 2231.22
#Mann=6,-1,0
  4675.4    0.07       0  4688.6   0.035       0  4810.1    0.07       0
  5005.6    0.07       0  5009.6    0.07       0  5181.4    0.16       0
Bank Sta=5005.6,5009.6
Exp/Cntr=0.3,0.1

Type RM Length L Ch R = 1,799,266,266,266
BEGIN DESCRIPTION:
Sweetwater Creek Trib 20T2_2 4382
END DESCRIPTION:
XS GIS Cut Line= 3
      1382122.89      6829838.87      1382270.22      6829638.51
      1382393.62      6829352.60
#Sta/Elev= 30
  4751.3 2212.87  4802.6 2212.31  4811.1 2211.48  4831.9 2211.60  4882.1 2208.50
  4902.9 2208.58  4958.8 2207.19  4982.4 2206.07  5011.4 2206.21  5024.2 2205.40
  5024.5 2204.90  5028.0 2204.90  5028.2 2205.40  5044.1 2206.51  5055.2 2208.55
  5102.2 2211.30  5120.3 2213.46  5125.7 2213.25  5131.3 2214.08  5142.1 2214.09
  5149.2 2214.94  5154.7 2214.61  5196.2 2218.56  5201.7 2218.35  5225.2 2221.40
  5230.6 2220.76  5254.1 2222.56  5272.2 2225.29  5283.7 2225.19  5311.4 2228.33
#Mann=4,-1,0
  4751.3    0.07       0  4958.8    0.16       0  5024.2    0.07       0
  5028.2    0.16       0
Bank Sta=5024.2,5028.2
Exp/Cntr=0.3,0.1

Type RM Length L Ch R = 1,533,213,213,213
BEGIN DESCRIPTION:
Sweetwater Creek Trib 20T2_2 2927
END DESCRIPTION:
XS GIS Cut Line= 3
      1382405.02      6829987.95      1382520.06      6829687.85
      1382555.00      6829387.98
#Sta/Elev= 30
  4678.6 2228.47  4710.7 2224.62  4729.0 2223.55  4785.6 2218.71  4803.0 2218.60
  4827.7 2215.66  4882.0 2211.45  4887.7 2210.16  4893.1 2210.09  4912.4 2207.24
  4935.6 2206.07  4942.4 2204.06  4967.1 2202.71  4970.5 2201.60  4970.7 2201.10
  4974.2 2201.10  4974.5 2201.60  4984.6 2201.63  5050.2 2202.70  5070.3 2206.00
  5083.6 2206.88  5090.7 2208.05  5110.6 2209.06  5150.9 2213.36  5181.1 2215.82
  5241.5 2219.58  5257.6 2222.08  5281.7 2223.23  5300.1 2225.65  5301.9 2225.65
#Mann=7,-1,0
  4678.6    0.07       0  4729.0   0.035       0  4970.5    0.07       0
  4974.5   0.035       0  4984.6    0.07       0  5083.6    0.16       0
  5300.1    0.07       0
Bank Sta=4970.5,4974.5
Exp/Cntr=0.3,0.1

Type RM Length L Ch R = 1,320,184,184,184
BEGIN DESCRIPTION:
Sweetwater Creek Trib 20T2_2 4381
END DESCRIPTION:
XS GIS Cut Line= 3
      1382630.02      6829919.17      1382714.65      6829748.84
      1382600.11      6829404.17
#Sta/Elev= 30
  4809.8 2213.33  4844.6 2211.28  4866.9 2208.45  4874.8 2208.71  4880.4 2206.94
  4885.8 2206.22  4919.7 2203.17  4942.1 2202.56  4964.5 2200.26  4970.0 2198.71
  4976.6 2198.61  4976.9 2198.11  4980.6 2198.61  5053.6 2199.74  5064.1 2201.80
  5073.8 2202.58  5079.0 2201.05  5105.4 2202.20  5110.7 2203.08  5116.8 2205.52
  5174.6 2209.16  5200.4 2212.40  5205.7 2212.31  5211.6 2214.15  5222.2 2215.23
  5232.1 2215.91  5237.4 2215.15  5295.4 2220.01  5300.7 2219.68  5363.2 2222.93
#Mann=5,-1,0
  4809.8    0.07       0  4885.8   0.035       0  4976.6   0.035       0
  4980.6   0.035       0  5174.6    0.07       0
Bank Sta=4976.6,4980.6
Exp/Cntr=0.3,0.1

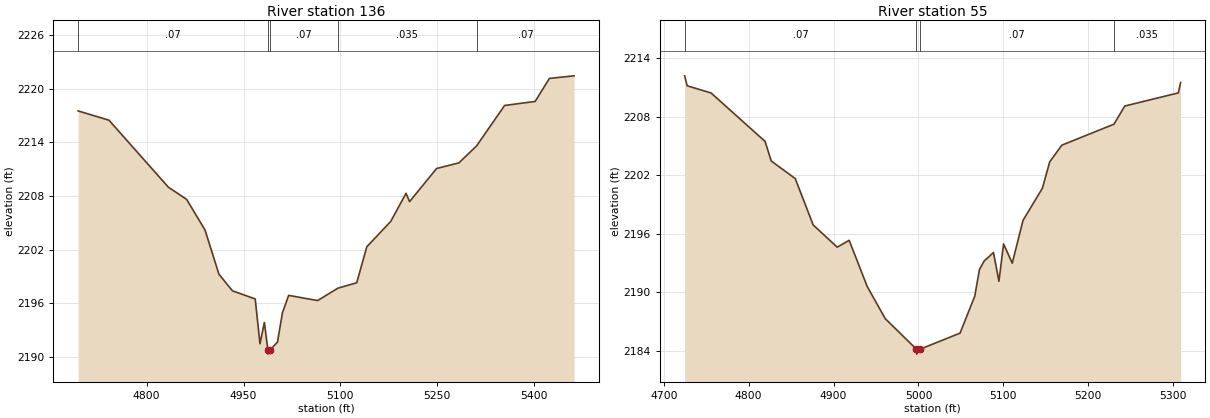
Type RM Length L Ch R = 1,136,81,81,81
BEGIN DESCRIPTION:
Sweetwater Creek Trib 20T2_2 4174
END DESCRIPTION:
XS GIS Cut Line= 3
      1382643.63      6830044.26      1382869.33      6829837.23
      1382688.36      6829412.89
#Sta/Elev= 30
  4694.0 2217.53  4741.8 2216.49  4833.7 2208.99  4862.0 2207.62  4890.4 2204.20
  4912.0 2199.24  4932.9 2197.38  4968.1 2196.47  4975.5 2191.45  4982.3 2193.84
  4987.7 2190.79  4987.9 2190.29  4991.7 2190.79  5002.6 2191.65  5010.3 2194.94
  5019.9 2196.87  5064.7 2196.29  5096.2 2197.68  5125.2 2198.28  5140.8 2202.31
  5177.9 2205.16  5201.5 2208.30  5207.0 2207.37  5248.8 2211.08  5283.3 2211.71
  5310.7 2213.61  5354.1 2218.14  5401.3 2218.59  5423.4 2221.17  5461.6 2221.46
#Mann=5,-1,0
  4694.0    0.07       0  4987.7    0.07       0  4991.7    0.07       0
  5096.2   0.035       0  5310.7    0.07       0
Bank Sta=4987.7,4991.7
Exp/Cntr=0.3,0.1

Type RM Length L Ch R = 1,55,0,0,0
BEGIN DESCRIPTION:
Sweetwater Creek Trib 20T2_2 482
END DESCRIPTION:
XS GIS Cut Line= 3
      1382758.08      6830035.27      1382950.40      6829838.14
      1382819.95      6829558.24
#Sta/Elev= 30
  4724.6 2212.21  4727.6 2211.19  4755.8 2210.45  4819.4 2205.48  4826.6 2203.48
  4854.9 2201.67  4876.0 2196.92  4904.3 2194.64  4918.4 2195.34  4939.7 2190.60
  4960.9 2187.31  4997.7 2184.17  4998.0 2183.67  5001.7 2184.17  5049.0 2185.82
  5066.3 2189.60  5071.9 2192.35  5077.4 2193.22  5088.4 2194.09  5094.8 2191.14
  5100.3 2194.97  5110.5 2193.00  5123.2 2197.39  5146.0 2200.68  5154.6 2203.38
  5168.9 2205.10  5230.3 2207.25  5243.0 2209.11  5306.1 2210.46  5308.8 2211.52
#Mann=4,-1,0
  4724.6    0.07       0  4997.7    0.07       0  5001.7    0.07       0
  5230.3   0.035       0
Bank Sta=4997.7,5001.7
Exp/Cntr=0.3,0.1

Chan Stop Cuts=-1