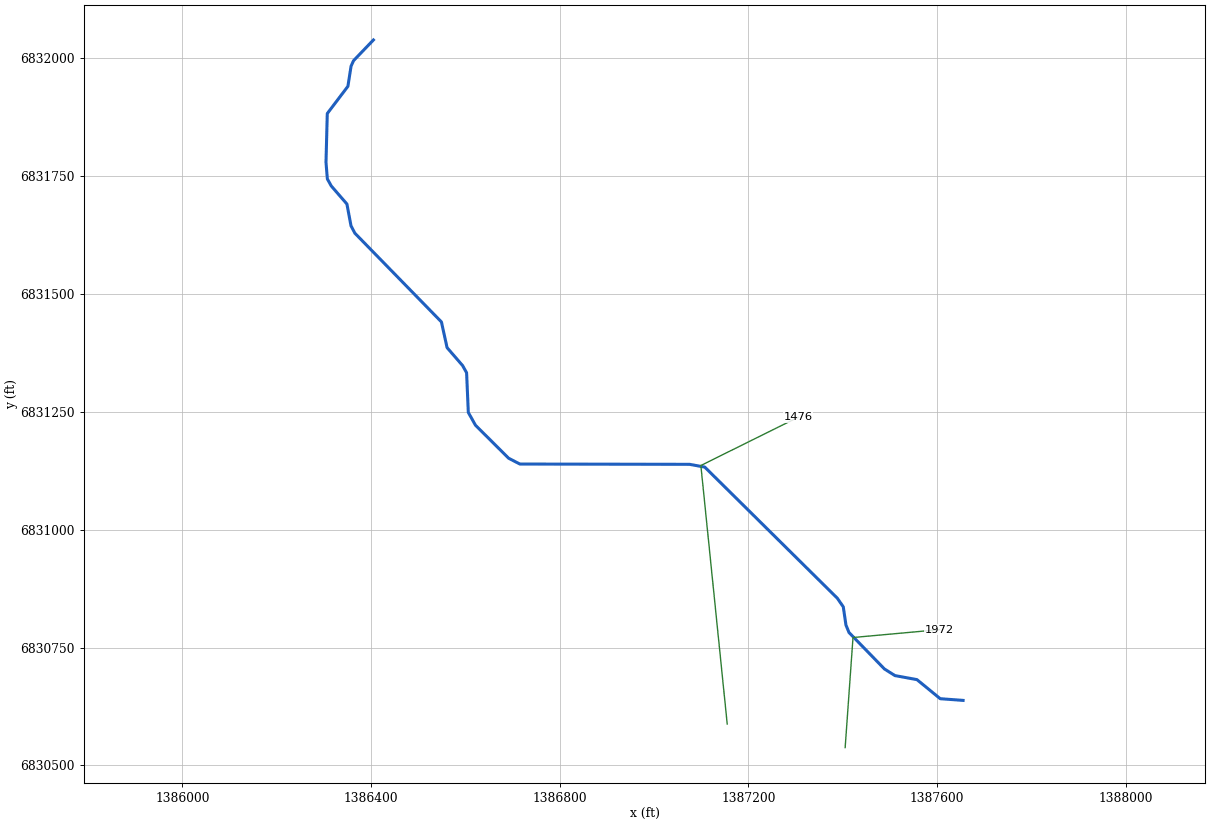
--- Sweetwater Creek Trib 20T3.prj (project) ---

Proj Title=Sweetwater Creek Trib 20T3 Base Level Engineering
Current Plan=p01
Default Exp/Contr=0.3,0.1
English Units
Geom File=g01
Flow File=f01
Plan File=p01
BEGIN DESCRIPTION:
Sweetwater Creek Trib 20T3
END DESCRIPTION:

--- Sweetwater Creek Trib 20T3.p01 (plan) ---

Plan Title=Multiple Run
Short Identifier=Multiple
Geom File=g01
Flow File=f01
Subcritical Flow
K Sum by GR= 0
Std Step Tol= 0.01
Critical Tol= 0.01
Num of Std Step Trials= 20
Max Error Tol= 0.3
Flow Tol Ratio= 0.001
Split Flow NTrial= 30
Split Flow Tol= 0.02
Split Flow Ratio= 0.02
Log Output Level= 0
Friction Slope Method= 1
Unsteady Friction Slope Method= 2
Unsteady Bridges Friction Slope Method= 1
Parabolic Critical Depth
Global Vel Dist=  1 , 1 , 1
Global Log Level= 0
CheckData=True
Encroach Param= -1, 0, 0, 0
BEGIN DESCRIPTION:
Multiple Run
END DESCRIPTION:

--- Sweetwater Creek Trib 20T3.f01 (steady flow) ---

Flow Title=Multiple
Number of Profiles=7
Profile Names=10-year,25-year,50-year,1pct_min,100-year,1pct_plu,500-year
River Rch & RM= Sweetwater Creek,Reach-1,1972
      87     115     136      81     162     323     230
Boundary for River Rch & Prof#=Sweetwater Creek,Reach-1,1
Up Type=0
Dn Type=3
Dn Slope=0.005
Boundary for River Rch & Prof#=Sweetwater Creek,Reach-1,2
Up Type=0
Dn Type=3
Dn Slope=0.005
Boundary for River Rch & Prof#=Sweetwater Creek,Reach-1,3
Up Type=0
Dn Type=3
Dn Slope=0.005
Boundary for River Rch & Prof#=Sweetwater Creek,Reach-1,4
Up Type=0
Dn Type=3
Dn Slope=0.005
Boundary for River Rch & Prof#=Sweetwater Creek,Reach-1,5
Up Type=0
Dn Type=3
Dn Slope=0.005
Boundary for River Rch & Prof#=Sweetwater Creek,Reach-1,6
Up Type=0
Dn Type=3
Dn Slope=0.005
Boundary for River Rch & Prof#=Sweetwater Creek,Reach-1,7
Up Type=0
Dn Type=3
Dn Slope=0.005

--- Sweetwater Creek Trib 20T3.g01 (geometry) ---

Geom Title=Existing Conditions

River Reach=Sweetwater Creek,Reach-1
Reach XY= 30
      1387655.00      6830638.00      1387606.49      6830641.60
      1387557.24      6830682.02      1387510.61      6830690.58
      1387488.29      6830704.62      1387413.15      6830781.93
      1387406.70      6830797.79      1387401.02      6830836.35
      1387388.35      6830854.67      1387107.45      6831132.54
      1387075.18      6831138.43      1386715.43      6831139.04
      1386691.65      6831151.36      1386621.44      6831221.21
      1386606.16      6831248.47      1386602.55      6831332.44
      1386594.16      6831347.65      1386561.14      6831385.83
      1386549.17      6831440.30      1386365.76      6831628.32
      1386357.50      6831644.03      1386348.86      6831690.17
      1386315.79      6831728.33      1386307.34      6831743.52
      1386304.49      6831778.74      1386307.22      6831882.07
      1386350.92      6831939.69      1386357.61      6831982.37
      1386362.91      6831994.15      1386405.00      6832038.00

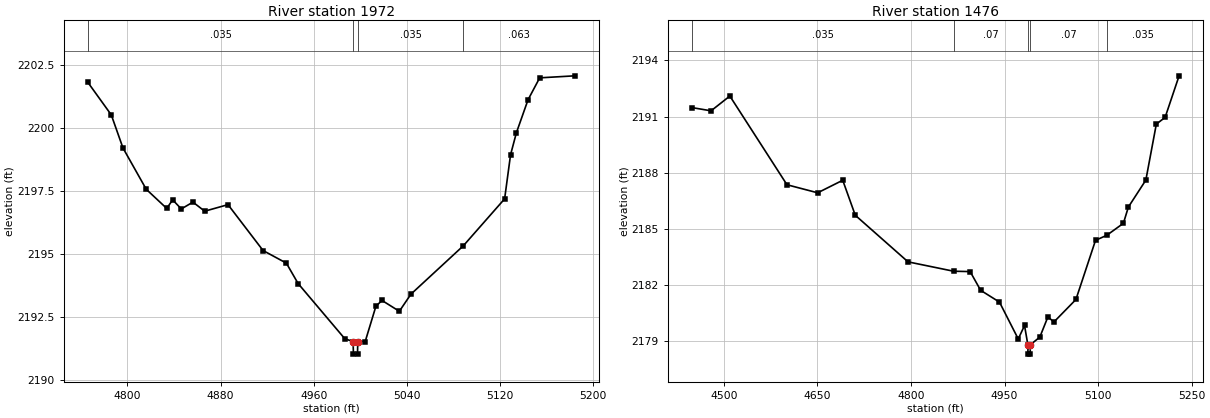
Type RM Length L Ch R = 1,1972,496,496,496
BEGIN DESCRIPTION:
Sweetwater Creek Trib 20T3 1.0
END DESCRIPTION:
XS GIS Cut Line= 3
      1387405.00      6830537.99      1387421.64      6830771.29
      1387604.98      6830788.00
#Sta/Elev= 30
  4766.1 2201.82  4786.2 2200.53  4796.2 2199.22  4816.2 2197.58  4833.8 2196.82
  4838.9 2197.16  4846.3 2196.80  4856.3 2197.07  4866.4 2196.71  4886.4 2196.97
  4916.5 2195.15  4936.5 2194.65  4946.6 2193.84  4986.7 2191.65  4993.8 2191.54
  4994.1 2191.04  4997.6 2191.04  4997.8 2191.54  5004.2 2191.54  5013.4 2192.94
  5018.6 2193.17  5033.5 2192.74  5043.5 2193.42  5088.5 2195.34  5123.9 2197.20
  5129.0 2198.95  5134.0 2199.82  5144.0 2201.13  5154.0 2202.00  5184.1 2202.08
#Mann=4,-1,0
  4766.1   0.035       0  4993.8   0.035       0  4997.8   0.035       0
  5088.5   0.063       0
Bank Sta=4993.8,4997.8
Exp/Cntr=0.3,0.1

Type RM Length L Ch R = 1,1476,0,0,0
BEGIN DESCRIPTION:
Sweetwater Creek Trib 20T3 2060
END DESCRIPTION:
XS GIS Cut Line= 3
      1387155.00      6830587.98      1387099.15      6831135.94
      1387305.03      6831238.02
#Sta/Elev= 30
  4449.2 2191.48  4479.4 2191.31  4509.5 2192.10  4601.1 2187.36  4650.3 2186.93
  4690.5 2187.60  4710.6 2185.73  4795.2 2183.24  4868.2 2182.74  4894.8 2182.72
  4911.6 2181.72  4941.8 2181.09  4971.9 2179.12  4982.0 2179.84  4987.3 2178.81
  4987.5 2178.31  4991.0 2178.31  4991.3 2178.81  5006.5 2179.22  5019.6 2180.31
  5028.9 2180.02  5064.4 2181.23  5095.8 2184.39  5113.9 2184.66  5140.5 2185.30
  5148.5 2186.17  5176.5 2187.61  5193.3 2190.60  5207.4 2190.96  5229.8 2193.18
#Mann=5,-1,0
  4449.2   0.035       0  4868.2    0.07       0  4987.3    0.07       0
  4991.3    0.07       0  5113.9   0.035       0
Bank Sta=4987.3,4991.3
Exp/Cntr=0.3,0.1

Chan Stop Cuts=-1