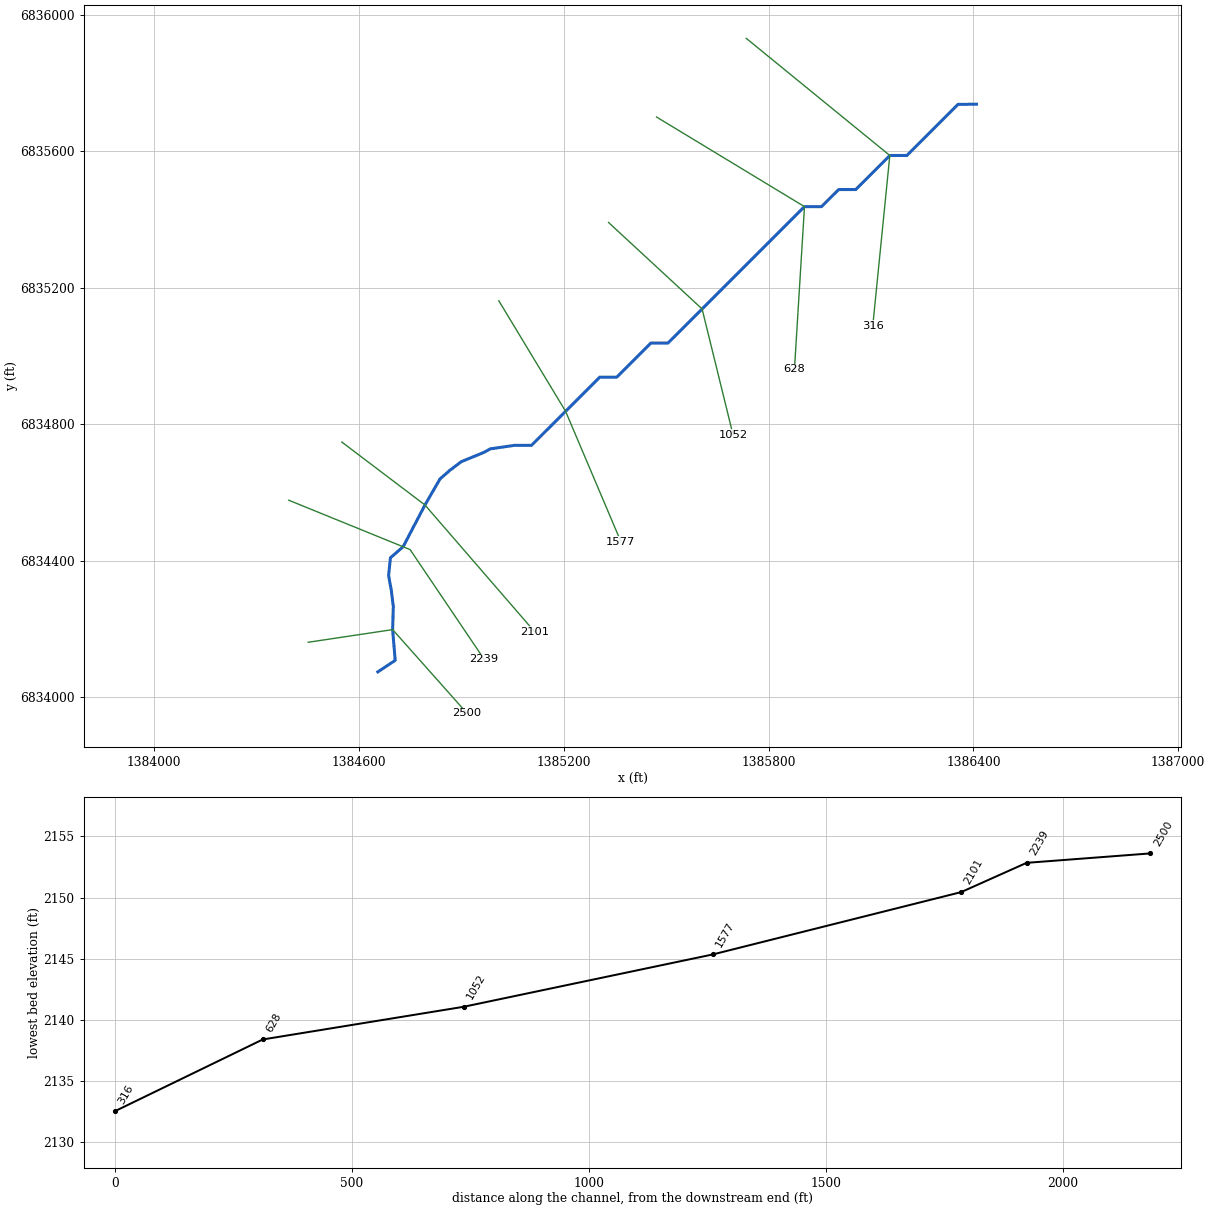
--- Sweetwater Creek Trib 20T4.5.prj (project) ---

Proj Title=Sweetwater Creek Trib 20T4.5 Base Level Engineering
Current Plan=p01
Default Exp/Contr=0.3,0.1
English Units
Geom File=g01
Flow File=f01
Plan File=p01
BEGIN DESCRIPTION:
Sweetwater Creek Trib 20T4.5
END DESCRIPTION:

--- Sweetwater Creek Trib 20T4.5.p01 (plan) ---

Plan Title=Multiple Run
Short Identifier=Multiple
Geom File=g01
Flow File=f01
Subcritical Flow
K Sum by GR= 0
Std Step Tol= 0.01
Critical Tol= 0.01
Num of Std Step Trials= 20
Max Error Tol= 0.3
Flow Tol Ratio= 0.001
Split Flow NTrial= 30
Split Flow Tol= 0.02
Split Flow Ratio= 0.02
Log Output Level= 0
Friction Slope Method= 1
Unsteady Friction Slope Method= 2
Unsteady Bridges Friction Slope Method= 1
Parabolic Critical Depth
Global Vel Dist=  1 , 1 , 1
Global Log Level= 0
CheckData=True
Encroach Param= -1, 0, 0, 0
BEGIN DESCRIPTION:
Multiple Run
END DESCRIPTION:

--- Sweetwater Creek Trib 20T4.5.f01 (steady flow) ---

Flow Title=Multiple
Number of Profiles=7
Profile Names=10-year,25-year,50-year,1pct_min,100-year,1pct_plu,500-year
River Rch & RM= Sweetwater Creek,Reach-1,2500
     126     172     208     126     251     501     370
Boundary for River Rch & Prof#=Sweetwater Creek,Reach-1,1
Up Type=0
Dn Type=3
Dn Slope=0.005
Boundary for River Rch & Prof#=Sweetwater Creek,Reach-1,2
Up Type=0
Dn Type=3
Dn Slope=0.005
Boundary for River Rch & Prof#=Sweetwater Creek,Reach-1,3
Up Type=0
Dn Type=3
Dn Slope=0.005
Boundary for River Rch & Prof#=Sweetwater Creek,Reach-1,4
Up Type=0
Dn Type=3
Dn Slope=0.005
Boundary for River Rch & Prof#=Sweetwater Creek,Reach-1,5
Up Type=0
Dn Type=3
Dn Slope=0.005
Boundary for River Rch & Prof#=Sweetwater Creek,Reach-1,6
Up Type=0
Dn Type=3
Dn Slope=0.005
Boundary for River Rch & Prof#=Sweetwater Creek,Reach-1,7
Up Type=0
Dn Type=3
Dn Slope=0.005

--- Sweetwater Creek Trib 20T4.5.g01 (geometry) ---

Geom Title=Existing Conditions

River Reach=Sweetwater Creek,Reach-1
Reach XY= 28
      1384654.95      6834073.87      1384705.83      6834107.55
      1384698.31      6834197.76      1384700.26      6834265.26
      1384694.50      6834312.12      1384686.48      6834356.42
      1384691.82      6834408.27      1384729.00      6834440.71
      1384793.03      6834563.15      1384837.01      6834639.42
      1384866.11      6834664.87      1384899.62      6834690.24
      1384966.22      6834717.61      1384984.03      6834727.68
      1385055.00      6834738.00      1385105.00      6834738.00
      1385305.00      6834938.00      1385355.00      6834938.00
      1385455.00      6835038.00      1385505.00      6835038.00
      1385905.00      6835438.00      1385955.00      6835438.00
      1386005.00      6835488.00      1386055.00      6835488.00
      1386155.00      6835588.00      1386205.00      6835588.00
      1386355.00      6835738.00      1386408.97      6835738.26

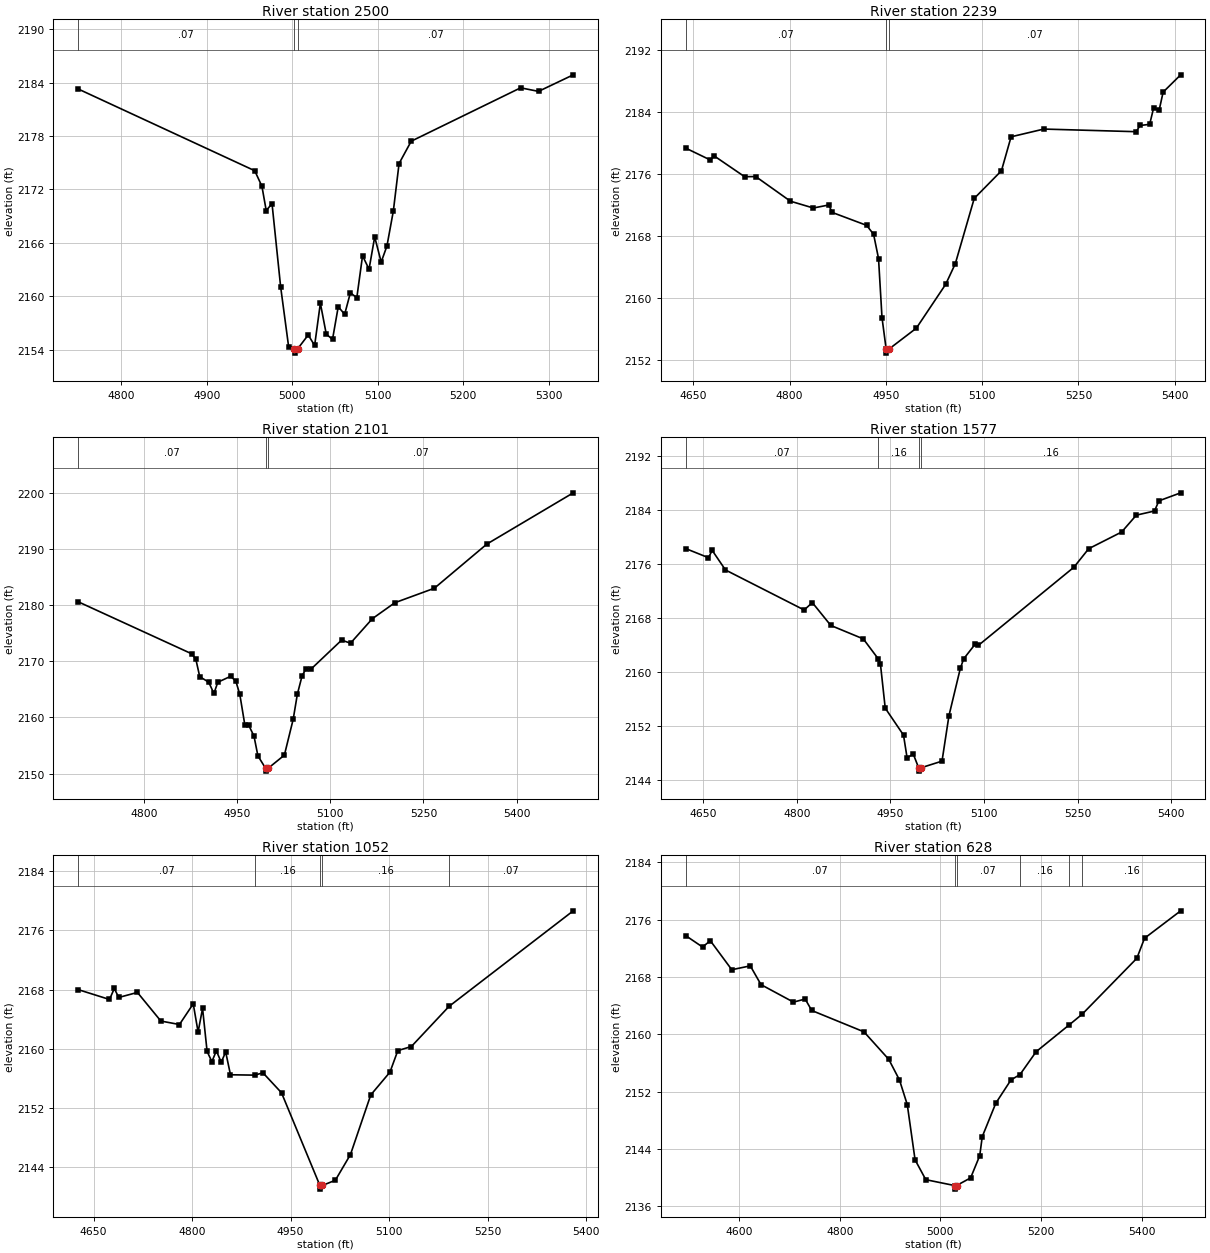
Type RM Length L Ch R = 1,2500,261,261,261
BEGIN DESCRIPTION:
Sweetwater Creek Trib 20T4.5 4070
END DESCRIPTION:
XS GIS Cut Line= 3
      1384450.88      6834160.67      1384698.31      6834197.76
      1384916.48      6833952.17
#Sta/Elev= 30
  4749.8 2183.29  4956.2 2174.10  4964.6 2172.35  4969.6 2169.63  4976.4 2170.40
  4986.5 2161.03  4995.8 2154.33  5002.5 2154.10  5002.7 2153.60  5006.5 2154.10
  5018.7 2155.64  5026.2 2154.46  5032.9 2159.21  5039.8 2155.74  5047.1 2155.14
  5053.8 2158.82  5061.3 2157.96  5068.0 2160.39  5075.5 2159.82  5082.2 2164.54
  5089.8 2163.03  5096.4 2166.66  5104.0 2163.84  5110.7 2165.63  5118.2 2169.57
  5124.9 2174.91  5139.1 2177.42  5267.0 2183.42  5287.9 2183.02  5328.5 2184.88
#Mann=3,-1,0
  4749.8    0.07       0  5002.5    0.07       0  5006.5    0.07       0
Bank Sta=5002.5,5006.5
Exp/Cntr=0.3,0.1

Type RM Length L Ch R = 1,2239,138,138,138
BEGIN DESCRIPTION:
Sweetwater Creek Trib 20T4.5 4069
END DESCRIPTION:
XS GIS Cut Line= 3
      1384393.74      6834577.26      1384749.55      6834432.34
      1384965.97      6834111.38
#Sta/Elev= 30
  4638.0 2179.30  4676.5 2177.76  4682.6 2178.28  4730.0 2175.60  4747.3 2175.62
  4801.3 2172.44  4837.0 2171.56  4861.0 2171.95  4866.4 2170.99  4920.1 2169.32
  4930.9 2168.17  4938.6 2165.04  4944.0 2157.42  4950.5 2153.33  4950.7 2152.83
  4954.5 2153.33  4997.5 2156.05  5043.2 2161.71  5058.2 2164.37  5087.7 2172.80
  5130.1 2176.37  5145.1 2180.75  5196.1 2181.75  5340.0 2181.41  5346.0 2182.21
  5361.0 2182.36  5367.0 2184.42  5375.9 2184.23  5382.0 2186.52  5409.3 2188.75
#Mann=3,-1,0
  4638.0    0.07       0  4950.5    0.07       0  4954.5    0.07       0
Bank Sta=4950.5,4954.5
Exp/Cntr=0.3,0.1

Type RM Length L Ch R = 1,2101,524,524,524
BEGIN DESCRIPTION:
Sweetwater Creek Trib 20T4.5 4068
END DESCRIPTION:
XS GIS Cut Line= 3
      1384549.53      6834747.65      1384793.03      6834563.15
      1385114.20      6834191.63
#Sta/Elev= 30
  4694.5 2180.61  4877.0 2171.35  4883.8 2170.39  4890.1 2167.27  4904.6 2166.28
  4912.9 2164.27  4919.2 2166.28  4940.0 2167.34  4948.3 2166.43  4954.6 2164.10
  4962.8 2158.59  4969.1 2158.57  4977.4 2156.68  4983.7 2153.16  4996.1 2150.94
  4996.3 2150.44  5000.1 2150.94  5026.3 2153.29  5040.5 2159.69  5047.2 2164.16
  5054.8 2167.42  5061.4 2168.72  5069.1 2168.61  5118.4 2173.78  5132.7 2173.23
  5167.8 2177.59  5204.0 2180.44  5267.6 2183.02  5352.1 2190.89  5491.1 2200.02
#Mann=3,-1,0
  4694.5    0.07       0  4996.1    0.07       0  5000.1    0.07       0
Bank Sta=4996.1,5000.1
Exp/Cntr=0.3,0.1

Type RM Length L Ch R = 1,1577,525,525,525
BEGIN DESCRIPTION:
Sweetwater Creek Trib 20T4.5 4067
END DESCRIPTION:
XS GIS Cut Line= 3
      1385009.47      6835161.85      1385205.00      6834838.00
      1385366.94      6834455.90
#Sta/Elev= 30
  4621.7 2178.28  4658.4 2176.92  4664.3 2178.01  4685.6 2175.11  4811.7 2169.19
  4824.8 2170.28  4854.4 2166.90  4906.5 2164.91  4930.5 2161.95  4934.0 2161.13
  4941.6 2154.67  4970.9 2150.68  4976.7 2147.28  4986.4 2147.91  4995.1 2145.85
  4995.3 2145.35  4999.1 2145.85  5032.6 2146.83  5043.7 2153.54  5061.9 2160.54
  5067.3 2161.96  5085.6 2164.12  5091.0 2163.96  5243.9 2175.51  5267.6 2178.25
  5320.4 2180.72  5344.0 2183.22  5373.1 2183.83  5380.1 2185.33  5415.0 2186.52
#Mann=4,-1,0
  4621.7    0.07       0  4930.5    0.16       0  4995.1    0.07       0
  4999.1    0.16       0
Bank Sta=4995.1,4999.1
Exp/Cntr=0.3,0.1

Type RM Length L Ch R = 1,1052,424,424,424
BEGIN DESCRIPTION:
Sweetwater Creek Trib 20T4.5 4066
END DESCRIPTION:
XS GIS Cut Line= 3
      1385330.90      6835391.56      1385605.00      6835138.00
      1385695.75      6834768.58
#Sta/Elev= 30
  4626.6 2168.00  4674.3 2166.67  4681.6 2168.15  4688.4 2166.94  4716.8 2167.62
  4752.5 2163.76  4780.8 2163.29  4801.8 2166.08  4809.2 2162.28  4816.0 2165.47
  4822.9 2159.66  4830.2 2158.28  4837.0 2159.74  4844.4 2158.20  4851.2 2159.59
  4858.5 2156.51  4895.7 2156.46  4907.9 2156.78  4936.2 2154.08  4994.6 2141.58
  4994.8 2141.08  4998.6 2141.58  5018.2 2142.28  5041.2 2145.75  5072.1 2153.79
  5101.3 2156.86  5113.3 2159.77  5133.9 2160.32  5191.3 2165.74  5380.4 2178.63
#Mann=5,-1,0
  4626.6    0.07       0  4895.7    0.16       0  4994.6    0.07       0
  4998.6    0.16       0  5191.3    0.07       0
Bank Sta=4994.6,4998.6
Exp/Cntr=0.3,0.1

Type RM Length L Ch R = 1,628,312,312,312
BEGIN DESCRIPTION:
Sweetwater Creek Trib 20T4.5 4065
END DESCRIPTION:
XS GIS Cut Line= 3
      1385471.61      6835700.71      1385905.00      6835438.00
      1385875.58      6834961.11
#Sta/Elev= 30
  4493.2 2173.80  4526.9 2172.20  4542.4 2173.08  4585.1 2169.03  4621.9 2169.57
  4643.2 2166.95  4707.7 2164.51  4731.0 2164.94  4744.1 2163.34  4848.0 2160.36
  4897.3 2156.52  4918.6 2153.64  4934.1 2150.20  4949.6 2142.50  4970.9 2139.73
  5028.1 2138.91  5028.3 2138.41  5032.1 2138.91  5060.1 2139.98  5078.2 2143.08
  5083.2 2145.73  5110.2 2150.41  5140.3 2153.65  5158.3 2154.40  5190.4 2157.59
  5256.6 2161.36  5281.9 2162.82  5390.7 2170.63  5405.9 2173.42  5477.8 2177.25
#Mann=6,-1,0
  4493.2    0.07       0  5028.1    0.07       0  5032.1    0.07       0
  5158.3    0.16       0  5256.6    0.07       0  5281.9    0.16       0
Bank Sta=5028.1,5032.1
Exp/Cntr=0.3,0.1

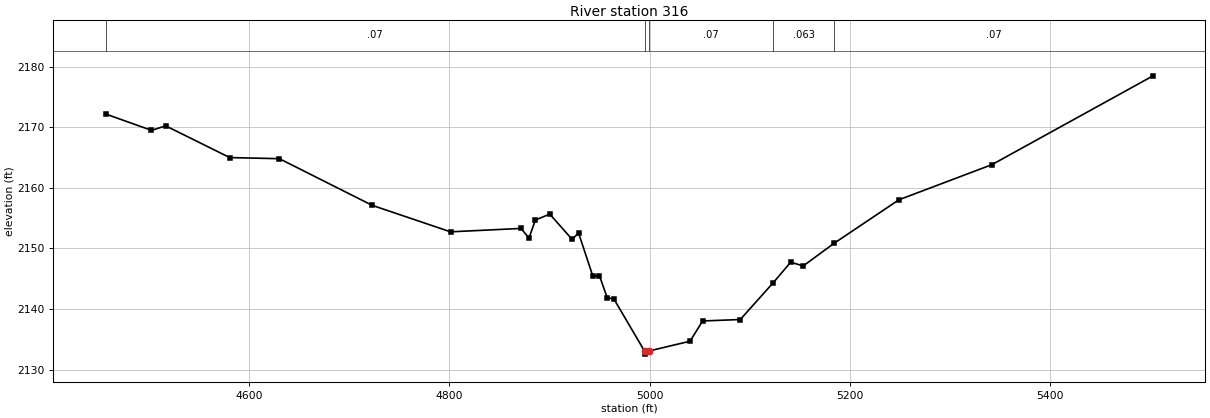
Type RM Length L Ch R = 1,316,0,0,0
BEGIN DESCRIPTION:
Sweetwater Creek Trib 20T4.5 4064
END DESCRIPTION:
XS GIS Cut Line= 3
      1385734.31      6835931.47      1386155.00      6835588.00
      1386105.00      6835087.99
#Sta/Elev= 30
  4456.9 2172.16  4502.5 2169.48  4516.8 2170.21  4580.7 2164.98  4630.2 2164.80
  4722.9 2157.10  4801.1 2152.73  4871.5 2153.29  4879.4 2151.69  4885.8 2154.68
  4900.2 2155.65  4922.5 2151.48  4928.9 2152.55  4943.3 2145.36  4949.7 2145.52
  4957.6 2141.83  4964.1 2141.68  4994.8 2133.05  4995.0 2132.55  4998.8 2133.05
  5040.2 2134.68  5052.8 2138.02  5090.4 2138.26  5123.2 2144.32  5140.7 2147.71
  5153.3 2147.11  5184.0 2150.83  5248.7 2158.01  5341.7 2163.82  5502.5 2178.47
#Mann=5,-1,0
  4456.9    0.07       0  4994.8    0.07       0  4998.8    0.07       0
  5123.2   0.063       0  5184.0    0.07       0
Bank Sta=4994.8,4998.8
Exp/Cntr=0.3,0.1

Chan Stop Cuts=-1