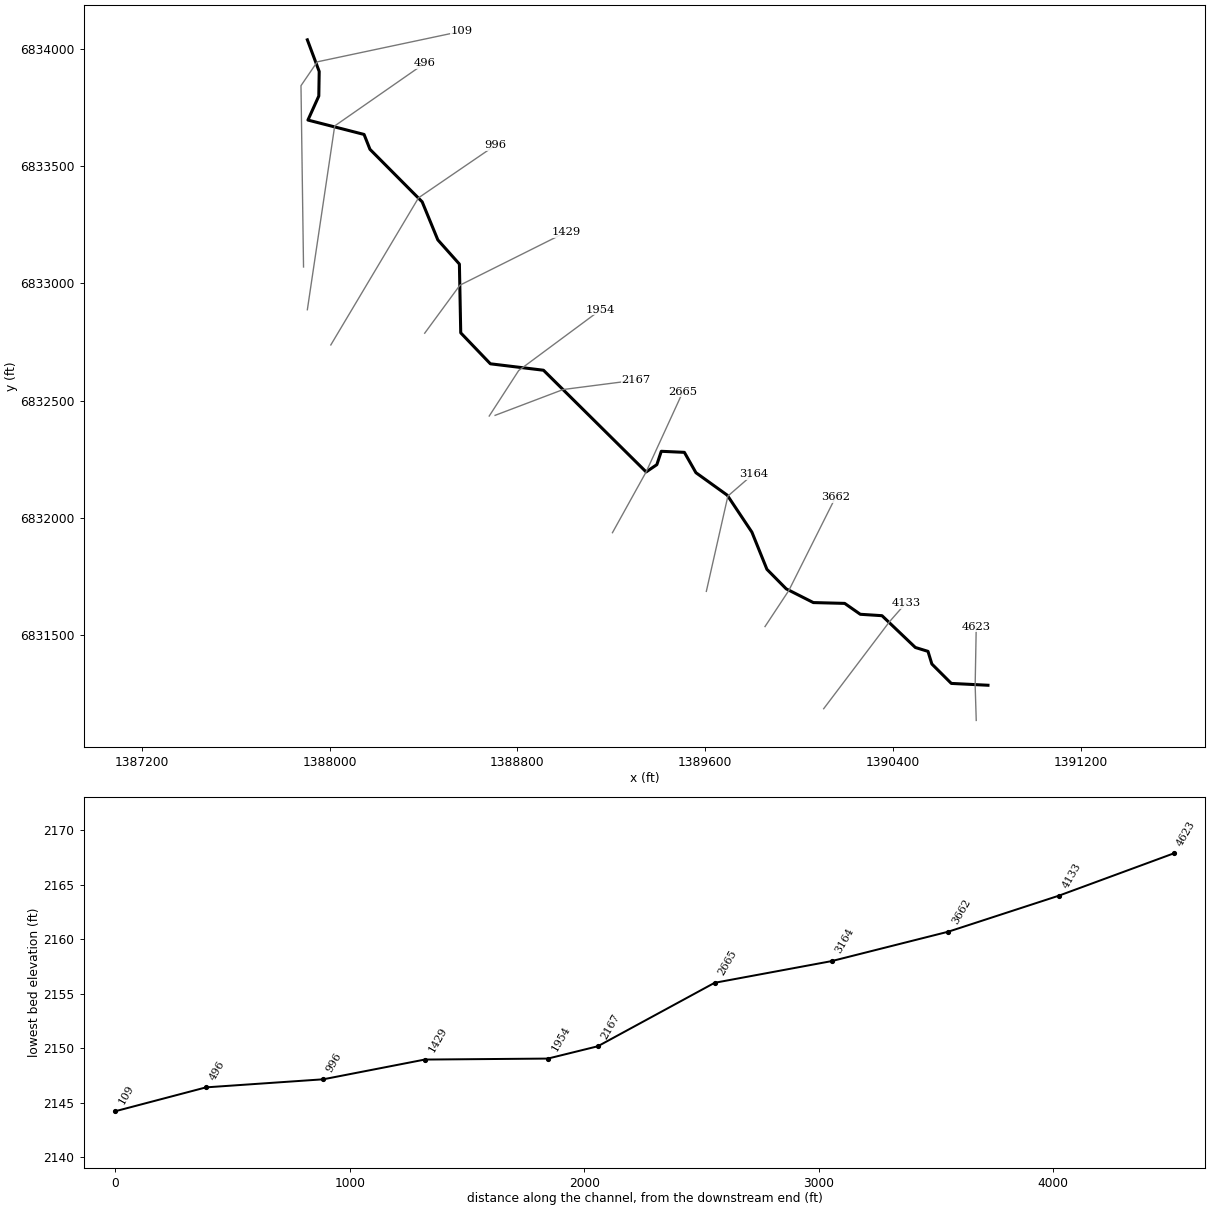
--- Sweetwater Creek Trib 20T4.prj (project) ---

Proj Title=Sweetwater Creek Trib 20T4 Base Level Engineering
Current Plan=p01
Default Exp/Contr=0.3,0.1
English Units
Geom File=g01
Flow File=f01
Plan File=p01
BEGIN DESCRIPTION:
Sweetwater Creek Trib 20T4
END DESCRIPTION:

--- Sweetwater Creek Trib 20T4.p01 (plan) ---

Plan Title=Multiple Run
Short Identifier=Multiple
Geom File=g01
Flow File=f01
Subcritical Flow
K Sum by GR= 0
Std Step Tol= 0.01
Critical Tol= 0.01
Num of Std Step Trials= 20
Max Error Tol= 0.3
Flow Tol Ratio= 0.001
Split Flow NTrial= 30
Split Flow Tol= 0.02
Split Flow Ratio= 0.02
Log Output Level= 0
Friction Slope Method= 1
Unsteady Friction Slope Method= 2
Unsteady Bridges Friction Slope Method= 1
Parabolic Critical Depth
Global Vel Dist=  1 , 1 , 1
Global Log Level= 0
CheckData=True
Encroach Param= -1, 0, 0, 0
BEGIN DESCRIPTION:
Multiple Run
END DESCRIPTION:

--- Sweetwater Creek Trib 20T4.f01 (steady flow) ---

Flow Title=Multiple
Number of Profiles=7
Profile Names=10-year,25-year,50-year,1pct_min,100-year,1pct_plu,500-year
River Rch & RM= Sweetwater Creek,Reach-1,4623
     441     646     824     522    1041    2078    1687
Boundary for River Rch & Prof#=Sweetwater Creek,Reach-1,1
Up Type=0
Dn Type=3
Dn Slope=0.005
Boundary for River Rch & Prof#=Sweetwater Creek,Reach-1,2
Up Type=0
Dn Type=3
Dn Slope=0.005
Boundary for River Rch & Prof#=Sweetwater Creek,Reach-1,3
Up Type=0
Dn Type=3
Dn Slope=0.005
Boundary for River Rch & Prof#=Sweetwater Creek,Reach-1,4
Up Type=0
Dn Type=3
Dn Slope=0.005
Boundary for River Rch & Prof#=Sweetwater Creek,Reach-1,5
Up Type=0
Dn Type=3
Dn Slope=0.005
Boundary for River Rch & Prof#=Sweetwater Creek,Reach-1,6
Up Type=0
Dn Type=3
Dn Slope=0.005
Boundary for River Rch & Prof#=Sweetwater Creek,Reach-1,7
Up Type=0
Dn Type=3
Dn Slope=0.005

--- Sweetwater Creek Trib 20T4.g01 (geometry) ---

Geom Title=Existing Conditions

River Reach=Sweetwater Creek,Reach-1
Reach XY= 30
      1390805.00      6831288.00      1390648.78      6831295.78
      1390565.88      6831378.56      1390549.38      6831432.38
      1390495.58      6831448.89      1390353.50      6831584.39
      1390260.98      6831590.36      1390194.49      6831636.77
      1390060.93      6831640.25      1389945.29      6831698.75
      1389863.13      6831781.93      1389799.15      6831940.29
      1389694.23      6832097.70      1389560.64      6832193.65
      1389511.39      6832280.33      1389413.05      6832284.81
      1389394.10      6832227.88      1389348.48      6832196.91
      1388911.19      6832630.19      1388684.83      6832657.60
      1388558.54      6832789.46      1388552.82      6833082.55
      1388460.85      6833185.71      1388394.24      6833347.68
      1388171.74      6833571.55      1388146.66      6833634.84
      1387907.49      6833696.15      1387953.77      6833798.48
      1387955.48      6833903.17      1387905.00      6834038.00

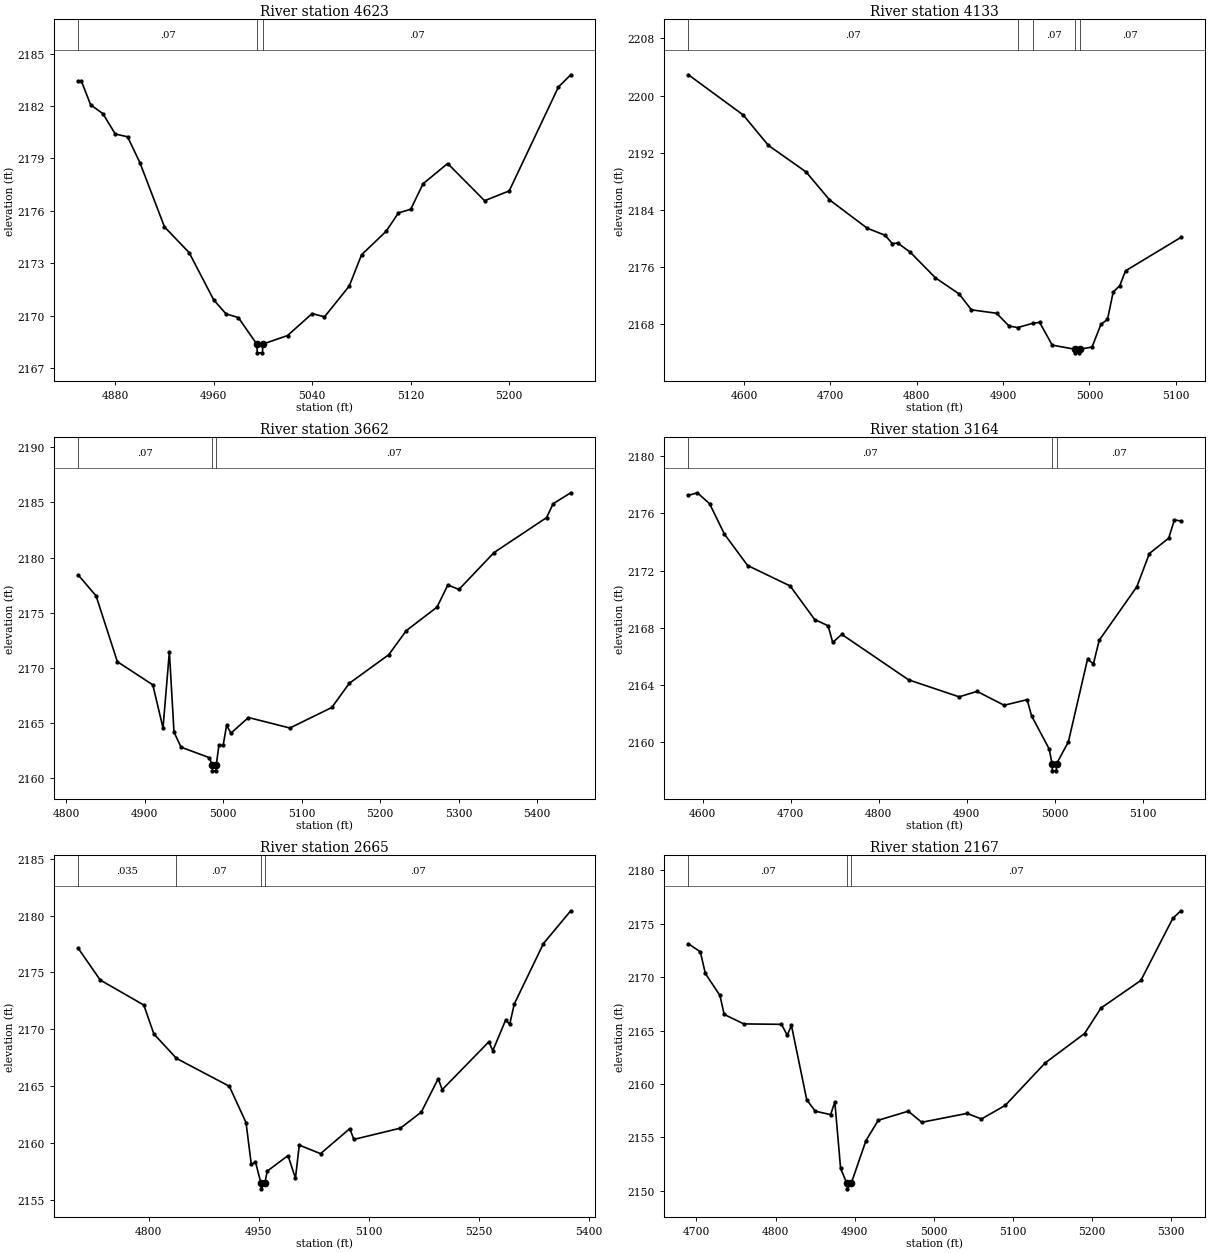
Type RM Length L Ch R = 1,4623,490,490,490
BEGIN DESCRIPTION:
Sweetwater Creek Trib 20T4 10.0
END DESCRIPTION:
XS GIS Cut Line= 3
      1390755.00      6831138.03      1390750.40      6831287.86
      1390755.00      6831538.02
#Sta/Elev= 30
  4850.1 2183.42  4852.6 2183.42  4860.1 2182.07  4870.1 2181.56  4880.1 2180.40
  4890.1 2180.24  4900.1 2178.76  4920.1 2175.08  4940.1 2173.61  4960.1 2170.90
  4970.1 2170.10  4980.1 2169.89  4995.1 2168.37  4995.5 2167.87  4999.7 2167.87
  5000.0 2168.37  5020.1 2168.86  5040.1 2170.12  5050.1 2169.93  5070.2 2171.69
  5080.2 2173.48  5100.2 2174.83  5110.2 2175.88  5120.2 2176.09  5130.2 2177.55
  5150.2 2178.71  5180.2 2176.58  5200.2 2177.14  5240.2 2183.09  5250.2 2183.79
#Mann=3,-1,0
  4850.1    0.07       0  4995.1    0.07       0  5000.0    0.07       0
Bank Sta=4995.1,5000
Exp/Cntr=0.3,0.1

Type RM Length L Ch R = 1,4133,471,471,471
BEGIN DESCRIPTION:
Sweetwater Creek Trib 20T4 9.0
END DESCRIPTION:
XS GIS Cut Line= 3
      1390105.00      6831188.00      1390385.20      6831558.48
      1390454.99      6831637.99
#Sta/Elev= 30
  4535.5 2202.91  4599.0 2197.28  4628.1 2193.03  4671.8 2189.31  4698.9 2185.41
  4742.5 2181.44  4763.4 2180.44  4771.7 2179.28  4777.9 2179.36  4792.5 2178.07
  4821.6 2174.49  4848.9 2172.25  4863.3 2170.01  4892.4 2169.53  4906.9 2167.74
  4916.9 2167.53  4934.5 2168.13  4942.3 2168.25  4956.9 2165.07  4983.4 2164.49
  4983.8 2163.99  4988.1 2163.99  4988.5 2164.49  5003.0 2164.80  5013.3 2167.97
  5020.9 2168.67  5027.5 2172.50  5035.1 2173.39  5041.8 2175.47  5105.8 2180.14
#Mann=5,-1,0
  4535.5    0.07       0  4916.9    0.16       0  4934.5    0.07       0
  4983.4    0.07       0  4988.5    0.07       0
Bank Sta=4983.4,4988.5
Exp/Cntr=0.3,0.1

Type RM Length L Ch R = 1,3662,498,498,498
BEGIN DESCRIPTION:
Sweetwater Creek Trib 20T4 8.0
END DESCRIPTION:
XS GIS Cut Line= 3
      1389854.98      6831537.96      1389956.62      6831691.94
      1390155.02      6832088.03
#Sta/Elev= 30
  4815.5 2178.42  4838.1 2176.54  4865.2 2170.58  4910.4 2168.48  4923.4 2164.57
  4931.5 2171.47  4937.4 2164.19  4946.5 2162.83  4982.6 2161.88  4986.0 2161.19
  4986.4 2160.69  4990.8 2160.69  4991.2 2161.19  4994.6 2162.99  5000.0 2162.99
  5004.4 2164.80  5010.0 2164.11  5032.3 2165.52  5085.1 2164.57  5138.5 2166.43
  5160.8 2168.62  5211.1 2171.21  5233.4 2173.39  5272.6 2175.52  5286.4 2177.53
  5300.5 2177.12  5345.2 2180.46  5412.2 2183.63  5420.6 2184.89  5443.0 2185.88
#Mann=3,-1,0
  4815.5    0.07       0  4986.0    0.07       0  4991.2    0.07       0
Bank Sta=4986,4991.2
Exp/Cntr=0.3,0.1

Type RM Length L Ch R = 1,3164,499,499,499
BEGIN DESCRIPTION:
Sweetwater Creek Trib 20T4 7.0
END DESCRIPTION:
XS GIS Cut Line= 3
      1389605.00      6831688.02      1389696.85      6832094.07
      1389805.04      6832188.03
#Sta/Elev= 30
  4583.7 2177.27  4593.9 2177.45  4607.8 2176.68  4624.7 2174.55  4651.0 2172.36
  4699.3 2170.93  4727.2 2168.58  4742.5 2168.14  4747.7 2166.98  4758.0 2167.54
  4833.9 2164.36  4891.3 2163.17  4911.8 2163.55  4942.5 2162.58  4968.6 2162.97
  4973.7 2161.84  4993.8 2159.51  4996.9 2158.49  4997.3 2157.99  5001.7 2157.99
  5002.1 2158.49  5015.5 2160.01  5037.3 2165.80  5044.0 2165.48  5050.6 2167.13
  5093.4 2170.88  5107.6 2173.20  5129.5 2174.27  5136.1 2175.56  5143.3 2175.47
#Mann=3,-1,0
  4583.7    0.07       0  4996.9    0.07       0  5002.1    0.07       0
Bank Sta=4996.9,5002.1
Exp/Cntr=0.3,0.1

Type RM Length L Ch R = 1,2665,498,498,498
BEGIN DESCRIPTION:
Sweetwater Creek Trib 20T4 6.0
END DESCRIPTION:
XS GIS Cut Line= 3
      1389205.00      6831938.01      1389348.48      6832196.91
      1389505.01      6832538.01
#Sta/Elev= 30
  4704.0 2177.11  4733.8 2174.34  4793.3 2172.14  4806.9 2169.61  4837.7 2167.46
  4909.8 2165.01  4932.6 2161.82  4939.8 2158.14  4945.5 2158.37  4952.9 2156.50
  4953.3 2156.00  4958.2 2156.50  4961.6 2157.56  4989.8 2158.92  5000.0 2156.94
  5005.2 2159.84  5034.2 2159.09  5074.1 2161.29  5079.6 2160.34  5143.1 2161.33
  5171.6 2162.74  5194.6 2165.67  5200.1 2164.71  5263.6 2168.91  5269.1 2168.14
  5286.6 2170.83  5292.1 2170.44  5298.3 2172.23  5338.1 2177.54  5375.3 2180.42
#Mann=4,-1,0
  4704.0   0.035       0  4837.7    0.07       0  4952.9    0.07       0
  4958.2    0.07       0
Bank Sta=4952.9,4958.2
Exp/Cntr=0.3,0.1

Type RM Length L Ch R = 1,2167,213,213,213
BEGIN DESCRIPTION:
Sweetwater Creek Trib 20T4 5.0
END DESCRIPTION:
XS GIS Cut Line= 3
      1388704.98      6832437.99      1388995.01      6832548.02
      1389305.04      6832588.01
#Sta/Elev= 30
  4689.8 2173.12  4704.9 2172.37  4711.2 2170.34  4729.7 2168.28  4735.0 2166.51
  4759.8 2165.62  4807.5 2165.58  4814.8 2164.56  4820.1 2165.48  4839.5 2158.51
  4850.3 2157.45  4869.7 2157.13  4875.0 2158.32  4882.3 2152.09  4890.3 2150.68
  4890.8 2150.18  4895.7 2150.68  4914.4 2154.70  4930.0 2156.60  4967.9 2157.45
  4984.9 2156.41  5042.1 2157.24  5060.5 2156.72  5090.7 2158.00  5141.1 2161.97
  5190.9 2164.72  5211.7 2167.11  5262.1 2169.69  5302.5 2175.50  5312.6 2176.21
#Mann=3,-1,0
  4689.8    0.07       0  4890.3    0.07       0  4895.7    0.07       0
Bank Sta=4890.3,4895.7
Exp/Cntr=0.3,0.1

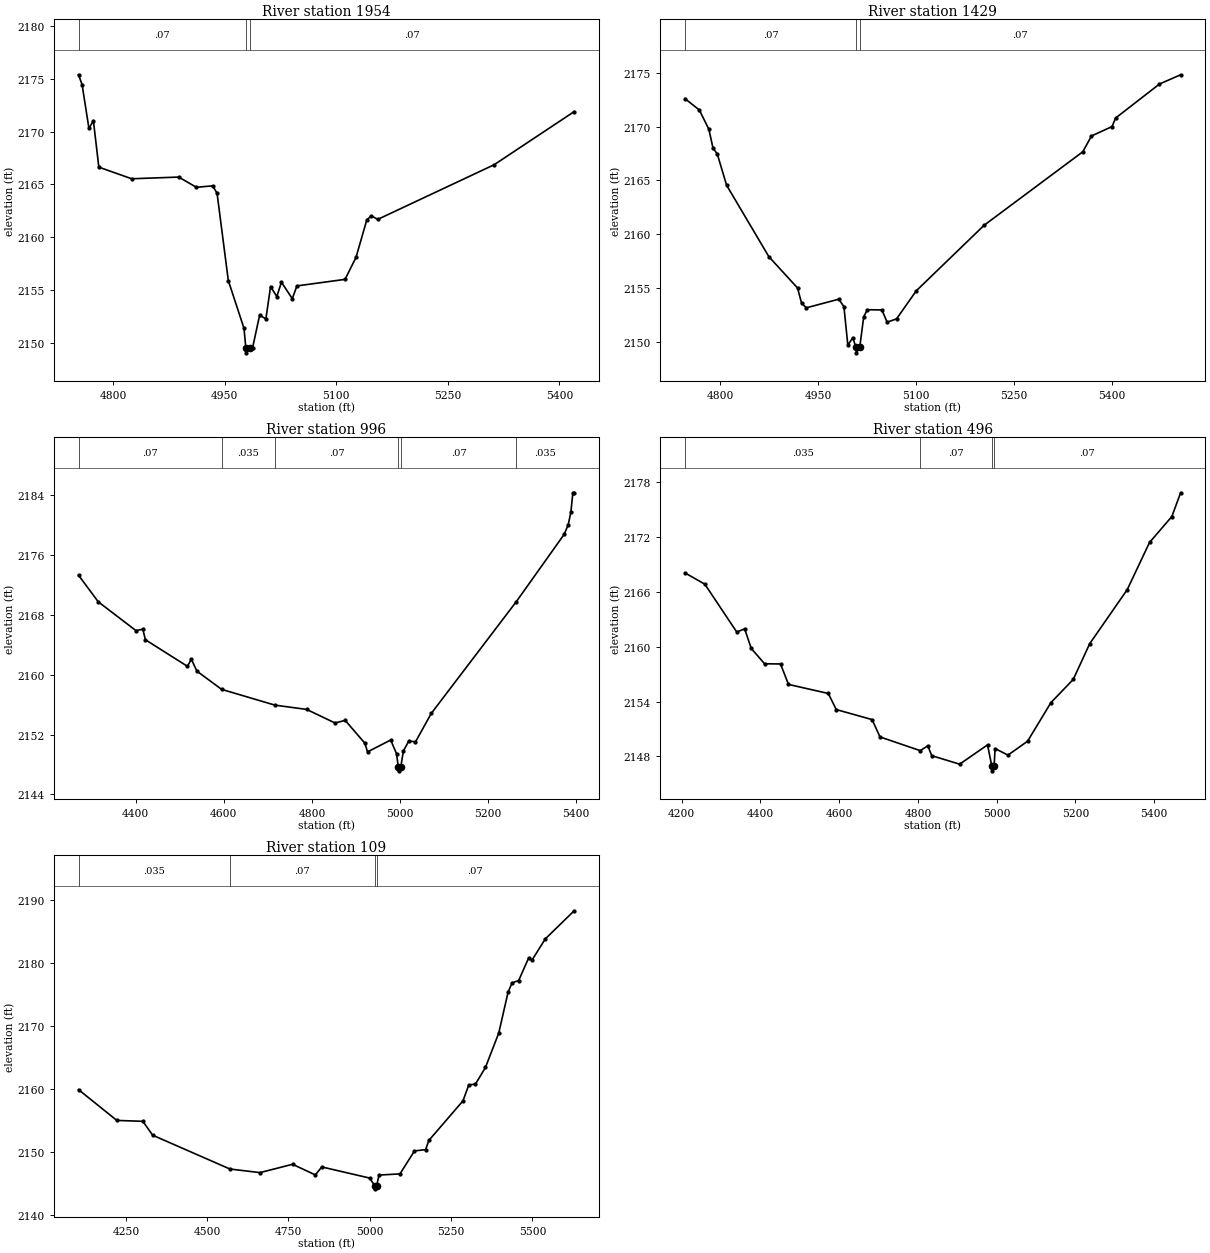
Type RM Length L Ch R = 1,1954,525,525,525
BEGIN DESCRIPTION:
Sweetwater Creek Trib 20T4 4.0
END DESCRIPTION:
XS GIS Cut Line= 3
      1388679.91      6832435.05      1388805.61      6832629.16
      1389155.02      6832888.01
#Sta/Elev= 30
  4753.7 2175.39  4758.5 2174.46  4767.7 2170.31  4773.7 2171.04  4781.0 2166.64
  4825.1 2165.54  4888.4 2165.70  4912.1 2164.73  4933.9 2164.87  4939.9 2164.17
  4955.0 2155.90  4976.1 2151.37  4978.5 2149.55  4979.0 2149.05  4984.0 2149.55
  4987.7 2149.55  4997.1 2152.62  5005.5 2152.26  5011.8 2155.33  5020.2 2154.38
  5026.4 2155.74  5041.0 2154.18  5047.2 2155.39  5111.9 2156.01  5126.6 2158.09
  5141.2 2161.66  5147.4 2162.03  5155.8 2161.69  5312.3 2166.87  5419.8 2171.90
#Mann=3,-1,0
  4753.7    0.07       0  4978.5    0.07       0  4984.0    0.07       0
Bank Sta=4978.5,4984
Exp/Cntr=0.3,0.1

Type RM Length L Ch R = 1,1429,433,433,433
BEGIN DESCRIPTION:
Sweetwater Creek Trib 20T4 3.0
END DESCRIPTION:
XS GIS Cut Line= 3
      1388405.02      6832788.03      1388555.09      6832992.58
      1389007.13      6833218.40
#Sta/Elev= 30
  4746.3 2172.60  4768.2 2171.55  4782.9 2169.75  4789.1 2168.03  4795.9 2167.43
  4810.0 2164.55  4874.8 2157.90  4918.7 2154.99  4924.9 2153.56  4932.3 2153.15
  4981.9 2153.95  4989.7 2153.25  4995.7 2149.66  5003.2 2150.37  5008.3 2149.46
  5008.7 2148.96  5013.9 2149.46  5020.0 2152.32  5025.6 2152.97  5047.9 2152.95
  5055.8 2151.81  5070.3 2152.12  5100.5 2154.73  5204.5 2160.83  5355.5 2167.66
  5368.8 2169.13  5400.2 2170.00  5405.8 2170.80  5472.9 2173.96  5505.3 2174.82
#Mann=3,-1,0
  4746.3    0.07       0  5008.3    0.07       0  5013.9    0.07       0
Bank Sta=5008.3,5013.9
Exp/Cntr=0.3,0.1

Type RM Length L Ch R = 1,996,500,500,500
BEGIN DESCRIPTION:
Sweetwater Creek Trib 20T4 2.0
END DESCRIPTION:
XS GIS Cut Line= 3
      1388004.98      6832737.97      1388378.71      6833364.82
      1388704.99      6833587.99
#Sta/Elev= 30
  4270.2 2173.30  4315.0 2169.74  4400.6 2165.89  4416.2 2166.08  4422.0 2164.67
  4517.4 2161.12  4526.4 2162.07  4538.8 2160.48  4595.0 2158.04  4716.1 2155.93
  4788.0 2155.36  4852.3 2153.55  4875.6 2153.89  4920.4 2150.83  4926.2 2149.68
  4978.8 2151.27  4992.1 2149.44  4996.1 2147.65  4996.6 2147.15  5001.7 2147.65
  5007.6 2149.80  5020.1 2151.15  5035.1 2151.02  5070.9 2154.82  5264.2 2169.78
  5372.9 2178.78  5381.8 2180.04  5387.9 2181.76  5392.3 2184.31  5395.3 2184.31
#Mann=6,-1,0
  4270.2    0.07       0  4595.0   0.035       0  4716.1    0.07       0
  4996.1    0.07       0  5001.7    0.07       0  5264.2   0.035       0
Bank Sta=4996.1,5001.7
Exp/Cntr=0.3,0.1

Type RM Length L Ch R = 1,496,387,387,387
BEGIN DESCRIPTION:
Sweetwater Creek Trib 20T4 1.0
END DESCRIPTION:
XS GIS Cut Line= 3
      1387905.00      6832888.01      1388021.54      6833671.08
      1388404.99      6833937.99
#Sta/Elev= 30
  4208.3 2168.08  4258.8 2166.84  4339.7 2161.61  4359.9 2161.95  4376.6 2159.81
  4410.5 2158.13  4451.0 2158.11  4471.2 2155.87  4572.3 2154.88  4592.5 2153.12
  4683.5 2152.02  4703.7 2150.12  4805.9 2148.62  4825.0 2149.15  4835.1 2148.07
  4905.9 2147.14  4976.7 2149.25  4987.8 2146.91  4988.3 2146.41  4993.5 2146.91
  4995.9 2148.85  5028.6 2148.13  5078.4 2149.65  5137.8 2153.88  5194.5 2156.42
  5236.4 2160.34  5331.5 2166.24  5388.2 2171.41  5444.9 2174.25  5467.2 2176.85
#Mann=4,-1,0
  4208.3   0.035       0  4805.9    0.07       0  4987.8    0.07       0
  4993.5    0.07       0
Bank Sta=4987.8,4993.5
Exp/Cntr=0.3,0.1

Type RM Length L Ch R = 1,109,0,0,0
BEGIN DESCRIPTION:
Sweetwater Creek Trib 20T4 4483
END DESCRIPTION:
XS GIS Cut Line= 4
      1387888.71      6833070.11      1387877.86      6833842.64
      1387947.11      6833944.16      1388561.85      6834074.47
#Sta/Elev= 30
  4104.5 2159.94  4222.4 2155.06  4302.4 2154.92  4332.4 2152.72  4570.1 2147.36
  4662.4 2146.79  4762.5 2148.11  4832.5 2146.43  4852.5 2147.69  4999.3 2145.93
  5015.4 2144.72  5015.9 2144.22  5021.1 2144.72  5028.5 2146.40  5092.9 2146.59
  5137.5 2150.23  5171.6 2150.43  5181.8 2151.90  5286.5 2158.16  5304.5 2160.69
  5324.9 2160.81  5355.6 2163.45  5396.5 2168.90  5425.2 2175.38  5437.4 2176.85
  5457.8 2177.23  5488.5 2180.81  5498.7 2180.46  5539.6 2183.82  5628.4 2188.28
#Mann=4,-1,0
  4104.5   0.035       0  4570.1    0.07       0  5015.4    0.07       0
  5021.1    0.07       0
Bank Sta=5015.4,5021.1
Exp/Cntr=0.3,0.1

Chan Stop Cuts=-1