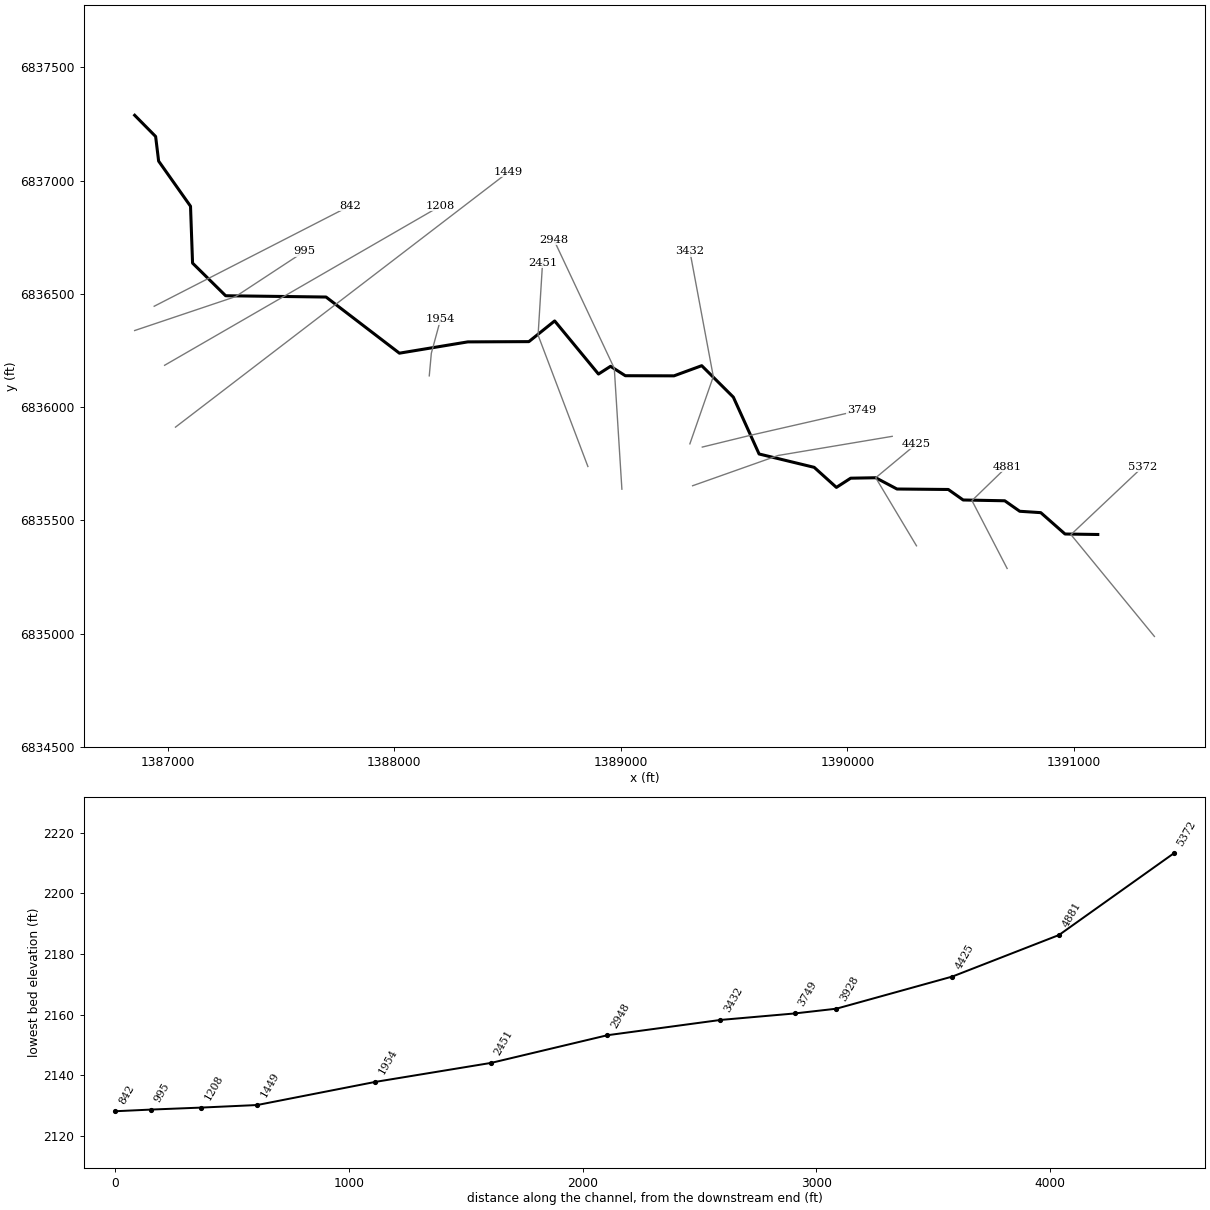
--- Sweetwater Creek Trib 20T5.prj (project) ---

Proj Title=Sweetwater Creek Trib 20T5 Base Level Engineering
Current Plan=p01
Default Exp/Contr=0.3,0.1
English Units
Geom File=g01
Flow File=f01
Plan File=p01
Y Axis Title=Elevation
X Axis Title(PF)=Main Channel Distance
X Axis Title(XS)=Station
BEGIN DESCRIPTION:
Sweetwater Creek Trib 20T5
END DESCRIPTION:
DSS Export Rating Curves= 0
DSS Export Rating Curve Sorted= 0
DSS Export Volume Flow Curves= 0
DXF OffsetX= 0
DXF OffsetY= 0
DXF ScaleX= 1
DXF ScaleY= 10

--- Sweetwater Creek Trib 20T5.p01 (plan) ---

Plan Title=Multiple Run
Short Identifier=Multiple
Geom File=g01
Flow File=f01
Subcritical Flow
K Sum by GR= 0
Std Step Tol= 0.01
Critical Tol= 0.01
Num of Std Step Trials= 20
Max Error Tol= 0.3
Flow Tol Ratio= 0.001
Split Flow NTrial= 30
Split Flow Tol= 0.02
Split Flow Ratio= 0.02
Log Output Level= 0
Friction Slope Method= 1
Unsteady Friction Slope Method= 2
Unsteady Bridges Friction Slope Method= 1
Parabolic Critical Depth
Global Vel Dist=  1 , 1 , 1
Global Log Level= 0
CheckData=True
Encroach Param= -1, 0, 0, 0
BEGIN DESCRIPTION:
Multiple Run
END DESCRIPTION:

--- Sweetwater Creek Trib 20T5.f01 (steady flow) ---

Flow Title=Multiple
Number of Profiles=7
Profile Names=10-year,25-year,50-year,1pct_min,100-year,1pct_plu,500-year
River Rch & RM= Sweetwater Creek,Reach-1,5372
     247     350     438     272     543    1084     848
Boundary for River Rch & Prof#=Sweetwater Creek,Reach-1,1
Up Type=0
Dn Type=3
Dn Slope=0.005
Boundary for River Rch & Prof#=Sweetwater Creek,Reach-1,2
Up Type=0
Dn Type=3
Dn Slope=0.005
Boundary for River Rch & Prof#=Sweetwater Creek,Reach-1,3
Up Type=0
Dn Type=3
Dn Slope=0.005
Boundary for River Rch & Prof#=Sweetwater Creek,Reach-1,4
Up Type=0
Dn Type=3
Dn Slope=0.005
Boundary for River Rch & Prof#=Sweetwater Creek,Reach-1,5
Up Type=0
Dn Type=3
Dn Slope=0.005
Boundary for River Rch & Prof#=Sweetwater Creek,Reach-1,6
Up Type=0
Dn Type=3
Dn Slope=0.005
Boundary for River Rch & Prof#=Sweetwater Creek,Reach-1,7
Up Type=0
Dn Type=3
Dn Slope=0.005

--- Sweetwater Creek Trib 20T5.g01 (geometry) ---

Geom Title=Existing Conditions

River Reach=Sweetwater Creek,Reach-1
Reach XY= 30
      1391105.00      6835438.00      1390960.43      6835440.13
      1390853.50      6835534.38      1390760.57      6835540.47
      1390694.50      6835586.78      1390510.94      6835590.26
      1390445.34      6835636.62      1390218.92      6835638.68
      1390125.13      6835688.39      1390014.59      6835686.46
      1389951.59      6835645.81      1389853.50      6835734.36
      1389610.44      6835793.25      1389496.86      6836044.06
      1389357.30      6836182.91      1389234.97      6836138.09
      1389020.16      6836138.65      1388954.90      6836180.19
      1388901.65      6836145.99      1388708.35      6836380.41
      1388594.57      6836289.06      1388325.03      6836287.93
      1388023.22      6836238.09      1387699.56      6836485.83
      1387256.46      6836491.54      1387110.46      6836635.55
      1387101.45      6836886.53      1386960.75      6837085.67
      1386947.50      6837194.32      1386855.00      6837288.00

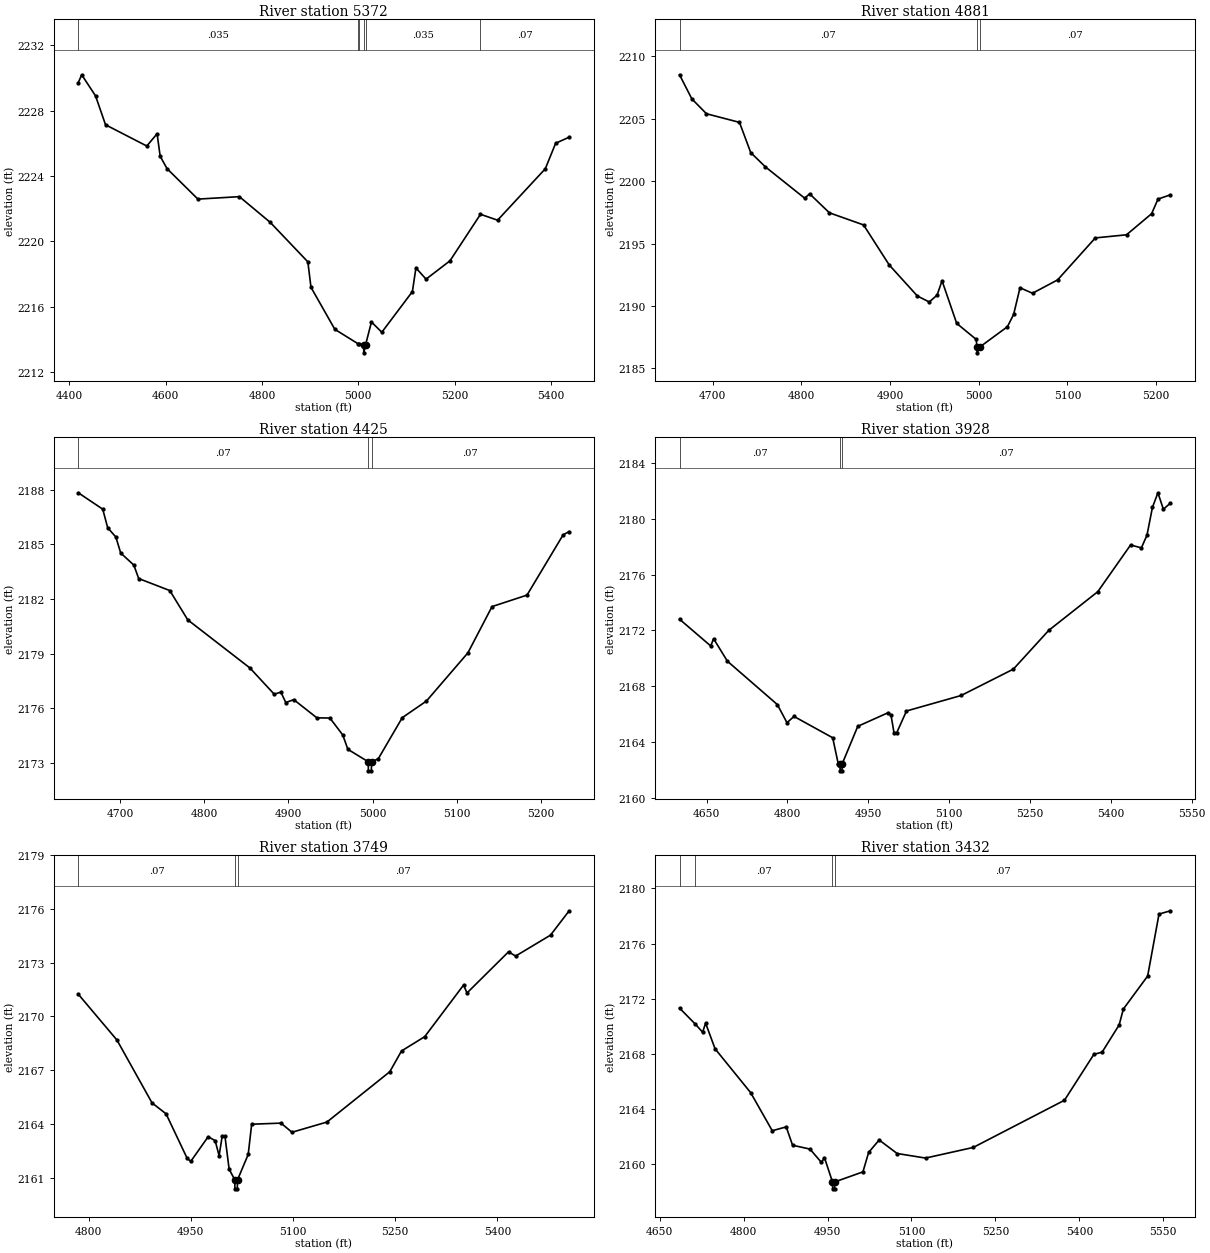
Type RM Length L Ch R = 1,5372,491,491,491
BEGIN DESCRIPTION:
Sweetwater Creek Trib 20T5 8.0
END DESCRIPTION:
XS GIS Cut Line= 3
      1391354.97      6834988.04      1390986.59      6835437.46
      1391304.97      6835737.97
#Sta/Elev= 30
  4418.9 2229.72  4426.0 2230.20  4454.7 2228.91  4475.5 2227.14  4561.1 2225.84
  4582.5 2226.59  4588.9 2225.21  4603.3 2224.45  4667.2 2222.59  4753.3 2222.74
  4817.2 2221.17  4895.4 2218.75  4901.9 2217.19  4951.4 2214.62  4998.8 2213.75
  5000.8 2213.75  5011.3 2213.68  5011.5 2213.18  5015.3 2213.68  5027.4 2215.07
  5048.9 2214.44  5112.4 2216.93  5119.7 2218.38  5140.7 2217.69  5190.3 2218.81
  5253.7 2221.66  5289.2 2221.30  5388.3 2224.45  5409.7 2226.01  5437.8 2226.38
#Mann=6,-1,0
  4418.9   0.035       0  4998.8    0.07       0  5000.8   0.035       0
  5011.3    0.07       0  5015.3   0.035       0  5253.7    0.07       0
Bank Sta=5011.3,5015.3
Exp/Cntr=0.3,0.1

Type RM Length L Ch R = 1,4881,456,456,456
BEGIN DESCRIPTION:
Sweetwater Creek Trib 20T5 7.0
END DESCRIPTION:
XS GIS Cut Line= 3
      1390705.01      6835287.98      1390549.82      6835587.57
      1390704.98      6835737.98
#Sta/Elev= 30
  4662.6 2208.51  4676.5 2206.58  4693.0 2205.39  4730.2 2204.70  4742.9 2202.28
  4759.4 2201.14  4803.7 2198.63  4809.3 2198.98  4831.6 2197.46  4870.1 2196.49
  4899.1 2193.28  4930.8 2190.80  4944.2 2190.32  4953.0 2190.87  4958.6 2192.02
  4975.1 2188.61  4997.2 2187.32  4997.8 2186.75  4998.1 2186.25  5001.8 2186.75
  5032.3 2188.34  5039.3 2189.32  5046.5 2191.46  5060.6 2191.02  5088.9 2192.09
  5131.4 2195.45  5166.6 2195.70  5194.9 2197.39  5202.1 2198.56  5216.1 2198.90
#Mann=3,-1,0
  4662.6    0.07       0  4997.8    0.07       0  5001.8    0.07       0
Bank Sta=4997.8,5001.8
Exp/Cntr=0.3,0.1

Type RM Length L Ch R = 1,4425,497,497,497
BEGIN DESCRIPTION:
Sweetwater Creek Trib 20T5 6.0
END DESCRIPTION:
XS GIS Cut Line= 3
      1390304.99      6835388.02      1390125.13      6835688.39
      1390305.03      6835838.03
#Sta/Elev= 30
  4649.9 2187.83  4679.0 2186.93  4684.9 2185.91  4694.6 2185.40  4700.4 2184.52
  4716.0 2183.86  4721.8 2183.12  4758.8 2182.46  4780.2 2180.85  4854.1 2178.21
  4883.0 2176.77  4891.0 2176.88  4896.8 2176.31  4906.3 2176.47  4933.8 2175.47
  4949.3 2175.46  4964.6 2174.53  4970.7 2173.74  4994.9 2173.06  4995.1 2172.56
  4998.6 2172.56  4998.9 2173.06  5006.8 2173.22  5035.4 2175.48  5064.1 2176.39
  5113.5 2179.04  5142.2 2181.58  5183.8 2182.21  5226.8 2185.52  5234.0 2185.70
#Mann=3,-1,0
  4649.9    0.07       0  4994.9    0.07       0  4998.9    0.07       0
Bank Sta=4994.9,4998.9
Exp/Cntr=0.3,0.1

Type RM Length L Ch R = 1,3928,179,179,179
BEGIN DESCRIPTION:
Sweetwater Creek Trib 20T5 5.0
END DESCRIPTION:
XS GIS Cut Line= 3
      1389317.07      6835653.10      1389694.34      6835786.62
      1390197.90      6835871.13
#Sta/Elev= 30
  4599.8 2172.81  4657.7 2170.89  4663.0 2171.41  4688.6 2169.80  4781.3 2166.69
  4799.2 2165.39  4812.2 2165.84  4884.0 2164.31  4894.3 2162.44  4897.6 2162.44
  4897.8 2161.94  4901.3 2161.94  4901.6 2162.44  4930.5 2165.13  4987.0 2166.11
  4992.3 2165.91  4997.7 2164.68  5002.9 2164.68  5020.9 2166.23  5122.3 2167.34
  5219.2 2169.23  5284.9 2172.01  5375.8 2174.78  5436.7 2178.13  5456.7 2177.92
  5467.1 2178.83  5477.2 2180.82  5487.4 2181.87  5497.5 2180.69  5510.6 2181.13
#Mann=3,-1,0
  4599.8    0.07       0  4897.6    0.07       0  4901.6    0.07       0
Bank Sta=4897.6,4901.6
Exp/Cntr=0.3,0.1

Type RM Length L Ch R = 1,3749,317,317,317
BEGIN DESCRIPTION:
Sweetwater Creek Trib 20T5 4071
END DESCRIPTION:
XS GIS Cut Line= 3
      1389359.79      6835823.76      1389568.94      6835874.86
      1390061.74      6835987.44
#Sta/Elev= 30
  4784.7 2171.24  4841.5 2168.68  4893.0 2165.17  4913.6 2164.56  4944.5 2162.08
  4949.8 2161.90  4975.4 2163.28  4985.7 2163.06  4991.5 2162.22  4996.1 2163.33
  5000.0 2163.33  5006.2 2161.47  5014.5 2160.87  5014.7 2160.37  5018.2 2160.37
  5018.5 2160.87  5034.2 2162.29  5039.3 2163.98  5082.3 2164.04  5098.5 2163.53
  5149.8 2164.10  5242.1 2166.91  5259.3 2168.07  5293.4 2168.87  5350.4 2171.75
  5355.5 2171.31  5416.5 2173.61  5426.8 2173.37  5478.1 2174.54  5505.5 2175.90
#Mann=3,-1,0
  4784.7    0.07       0  5014.5    0.07       0  5018.5    0.07       0
Bank Sta=5014.5,5018.5
Exp/Cntr=0.3,0.1

Type RM Length L Ch R = 1,3432,484,484,484
BEGIN DESCRIPTION:
Sweetwater Creek Trib 20T5 4.0
END DESCRIPTION:
XS GIS Cut Line= 3
      1389305.00      6835838.00      1389408.42      6836134.91
      1389305.00      6836688.02
#Sta/Elev= 30
  4685.6 2171.33  4713.5 2170.18  4726.9 2169.58  4732.2 2170.24  4749.1 2168.38
  4812.7 2165.20  4851.3 2162.44  4876.2 2162.72  4887.6 2161.39  4918.7 2161.11
  4939.2 2160.14  4944.5 2160.50  4958.9 2158.73  4959.2 2158.23  4962.7 2158.23
  4962.9 2158.73  5013.3 2159.46  5023.5 2160.87  5042.3 2161.77  5074.4 2160.79
  5125.2 2160.46  5210.4 2161.23  5373.4 2164.65  5426.0 2167.98  5440.6 2168.13
  5471.1 2170.11  5478.6 2171.26  5522.0 2173.65  5542.3 2178.14  5562.7 2178.38
#Mann=4,-1,0
  4685.6   0.035       0  4713.5    0.07       0  4958.9    0.07       0
  4962.9    0.07       0
Bank Sta=4958.9,4962.9
Exp/Cntr=0.3,0.1

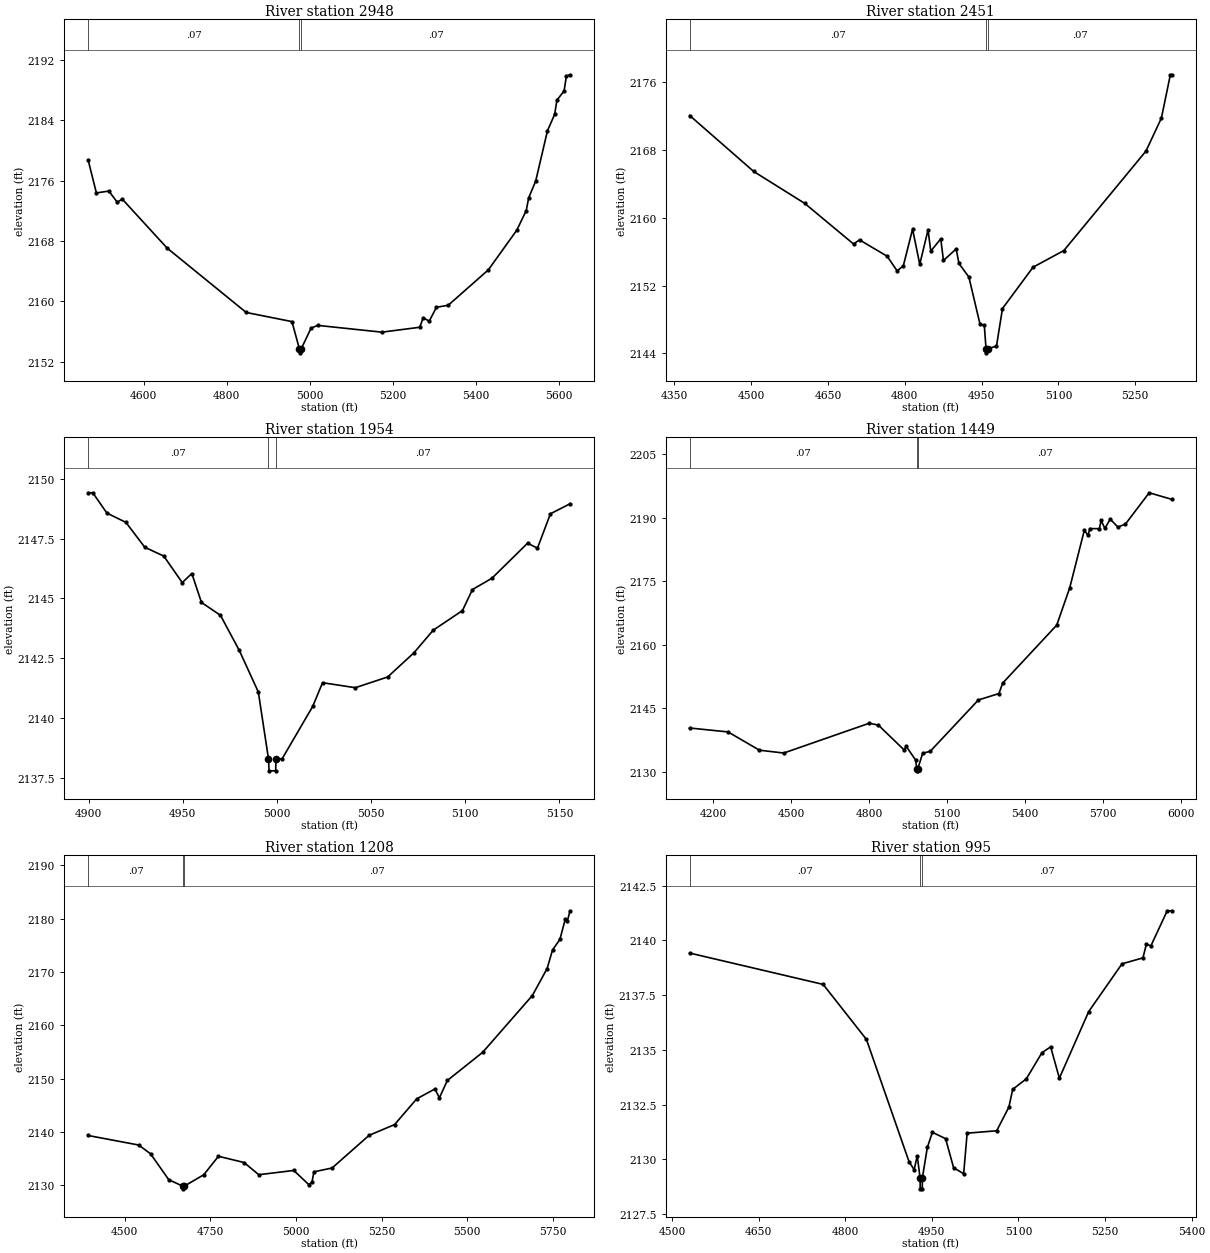
Type RM Length L Ch R = 1,2948,497,497,497
BEGIN DESCRIPTION:
Sweetwater Creek Trib 20T5 3.0
END DESCRIPTION:
XS GIS Cut Line= 3
      1389005.00      6835638.00      1388971.47      6836171.14
      1388704.99      6836738.03
#Sta/Elev= 30
  4465.8 2178.78  4485.8 2174.38  4515.9 2174.63  4535.9 2173.16  4548.2 2173.56
  4656.2 2167.07  4846.6 2158.54  4956.8 2157.33  4974.8 2153.69  4975.1 2153.19
  4978.8 2153.69  5002.8 2156.46  5018.6 2156.83  5173.4 2155.93  5264.6 2156.58
  5272.8 2157.85  5287.4 2157.38  5304.7 2159.23  5333.0 2159.49  5429.8 2164.19
  5498.2 2169.44  5521.0 2172.04  5526.9 2173.74  5543.8 2175.96  5572.1 2182.62
  5589.4 2184.79  5594.9 2186.68  5612.2 2187.90  5617.7 2189.88  5626.4 2190.04
#Mann=3,-1,0
  4465.8    0.07       0  4974.8    0.07       0  4978.8    0.07       0
Bank Sta=4974.8,4978.8
Exp/Cntr=0.3,0.1

Type RM Length L Ch R = 1,2451,497,497,497
BEGIN DESCRIPTION:
Sweetwater Creek Trib 20T5 2.0
END DESCRIPTION:
XS GIS Cut Line= 3
      1388854.98      6835738.04      1388635.20      6836317.67
      1388655.00      6836637.96
#Sta/Elev= 30
  4380.1 2172.03  4505.0 2165.44  4604.6 2161.68  4700.0 2156.89  4711.6 2157.38
  4765.6 2155.45  4785.1 2153.72  4797.2 2154.34  4815.2 2158.64  4829.2 2154.50
  4845.4 2158.56  4850.7 2156.05  4870.2 2157.50  4875.5 2154.95  4900.3 2156.31
  4905.7 2154.60  4925.1 2153.00  4946.9 2147.43  4955.2 2147.31  4958.6 2144.57
  4958.8 2144.07  4962.6 2144.57  4979.0 2144.86  4990.7 2149.29  5050.4 2154.16
  5110.5 2156.12  5270.8 2167.84  5300.9 2171.72  5318.4 2176.83  5320.9 2176.83
#Mann=3,-1,0
  4380.1    0.07       0  4958.6    0.07       0  4962.6    0.07       0
Bank Sta=4958.6,4962.6
Exp/Cntr=0.3,0.1

Type RM Length L Ch R = 1,1954,505,505,505
BEGIN DESCRIPTION:
Sweetwater Creek Trib 20T5 1.0
END DESCRIPTION:
XS GIS Cut Line= 3
      1388155.00      6836138.00      1388164.13      6836237.88
      1388205.01      6836388.02
#Sta/Elev= 30
  4899.7 2149.42  4902.2 2149.42  4909.7 2148.57  4919.8 2148.18  4929.8 2147.14
  4939.9 2146.77  4949.7 2145.66  4954.8 2146.04  4959.9 2144.83  4970.0 2144.29
  4980.0 2142.82  4990.1 2141.08  4995.5 2138.28  4995.8 2137.78  4999.3 2137.78
  4999.5 2138.28  5002.7 2138.28  5019.0 2140.48  5024.2 2141.47  5041.6 2141.26
  5058.8 2141.71  5072.7 2142.72  5083.0 2143.67  5098.5 2144.49  5103.8 2145.37
  5114.1 2145.84  5133.1 2147.31  5138.3 2147.10  5145.2 2148.54  5155.6 2148.96
#Mann=3,-1,0
  4899.7    0.07       0  4995.5    0.07       0  4999.5    0.07       0
Bank Sta=4995.5,4999.5
Exp/Cntr=0.3,0.1

Type RM Length L Ch R = 1,1449,241,241,241
BEGIN DESCRIPTION:
Sweetwater Creek Trib 20 16.0
END DESCRIPTION:
XS GIS Cut Line= 2
      1387035.10      6835911.70      1388505.00      6837038.00
#Sta/Elev= 30
  4110.7 2140.29  4258.1 2139.36  4378.7 2135.04  4472.1 2134.37  4800.3 2141.41
  4835.6 2140.98  4935.3 2135.06  4942.0 2136.00  4978.9 2132.70  4983.2 2130.66
  4983.4 2130.16  4987.2 2130.66  5006.0 2134.32  5035.0 2134.78  5220.0 2146.92
  5298.9 2148.43  5313.4 2150.91  5521.0 2164.61  5570.9 2173.43  5627.0 2187.04
  5641.6 2185.81  5647.9 2187.43  5685.1 2187.43  5691.4 2189.38  5705.9 2187.51
  5726.8 2189.67  5755.8 2187.81  5784.8 2188.49  5876.3 2195.91  5962.5 2194.37
#Mann=3,-1,0
  4110.7    0.07       0  4983.2    0.07       0  4987.2    0.07       0
Bank Sta=4983.2,4987.2
Exp/Cntr=0.3,0.1

Type RM Length L Ch R = 1,1208,213,213,213
BEGIN DESCRIPTION:
Sweetwater Creek Trib 20 15.0
END DESCRIPTION:
XS GIS Cut Line= 2
      1386987.13      6836184.65      1388205.01      6836888.01
#Sta/Elev= 30
  4393.4 2139.32  4541.1 2137.53  4575.8 2135.88  4628.9 2131.02  4670.0 2129.81
  4670.2 2129.31  4674.0 2129.81  4730.8 2131.94  4773.9 2135.42  4848.5 2134.25
  4891.6 2131.96  4993.6 2132.76  5037.6 2130.10  5046.7 2130.52  5052.4 2132.50
  5105.5 2133.22  5213.3 2139.34  5287.9 2141.37  5352.5 2146.20  5405.6 2148.05
  5418.7 2146.39  5441.8 2149.64  5544.9 2154.92  5689.9 2165.58  5733.0 2170.64
  5748.8 2174.13  5770.4 2176.12  5786.1 2179.94  5791.9 2179.50  5799.8 2181.48
#Mann=3,-1,0
  4393.4    0.07       0  4670.0    0.07       0  4674.0    0.07       0
Bank Sta=4670,4674
Exp/Cntr=0.3,0.1

Type RM Length L Ch R = 1,995,153,153,153
BEGIN DESCRIPTION:
Sweetwater Creek Trib 20T5 2704
END DESCRIPTION:
XS GIS Cut Line= 3
      1386854.96      6836337.99      1387299.80      6836487.52
      1387605.04      6836688.03
#Sta/Elev= 30
  4530.7 2139.42  4761.8 2137.99  4836.7 2135.48  4910.5 2129.90  4919.4 2129.53
  4924.7 2130.17  4929.6 2129.16  4929.9 2128.66  4933.4 2128.66  4933.6 2129.16
  4942.2 2130.55  4950.9 2131.24  4973.8 2130.95  4987.7 2129.62  5005.1 2129.35
  5011.1 2131.20  5062.3 2131.31  5083.4 2132.39  5090.0 2133.20  5113.6 2133.68
  5140.6 2134.87  5155.7 2135.14  5170.8 2133.71  5221.6 2136.75  5279.3 2138.93
  5315.5 2139.20  5321.4 2139.82  5329.3 2139.75  5357.6 2141.35  5365.2 2141.35
#Mann=3,-1,0
  4530.7    0.07       0  4929.6    0.07       0  4933.6    0.07       0
Bank Sta=4929.6,4933.6
Exp/Cntr=0.3,0.1

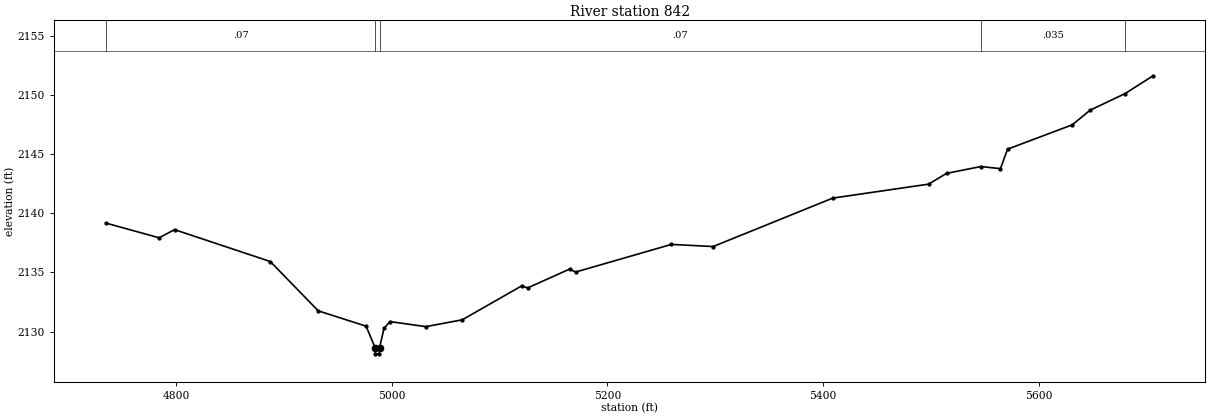
Type RM Length L Ch R = 1,842,0,0,0
BEGIN DESCRIPTION:
Sweetwater Creek Trib 20 14.0
END DESCRIPTION:
XS GIS Cut Line= 2
      1386941.20      6836445.18      1387805.01      6836888.00
#Sta/Elev= 30
  4735.2 2139.17  4784.4 2137.93  4798.7 2138.62  4887.5 2135.92  4931.9 2131.75
  4976.3 2130.45  4984.7 2128.61  4984.9 2128.11  4988.4 2128.11  4988.7 2128.61
  4992.9 2130.28  4998.5 2130.84  5031.6 2130.41  5065.4 2130.99  5120.5 2133.86
  5126.1 2133.69  5164.9 2135.28  5170.5 2135.03  5259.3 2137.37  5298.0 2137.19
  5409.0 2141.29  5497.8 2142.47  5514.4 2143.38  5546.2 2143.96  5564.4 2143.78
  5571.0 2145.43  5631.0 2147.49  5647.6 2148.73  5680.1 2150.14  5705.9 2151.64
#Mann=5,-1,0
  4735.2    0.07       0  4984.7    0.07       0  4988.7    0.07       0
  5546.2   0.035       0  5680.1    0.07       0
Bank Sta=4984.7,4988.7
Exp/Cntr=0.3,0.1

Chan Stop Cuts=-1