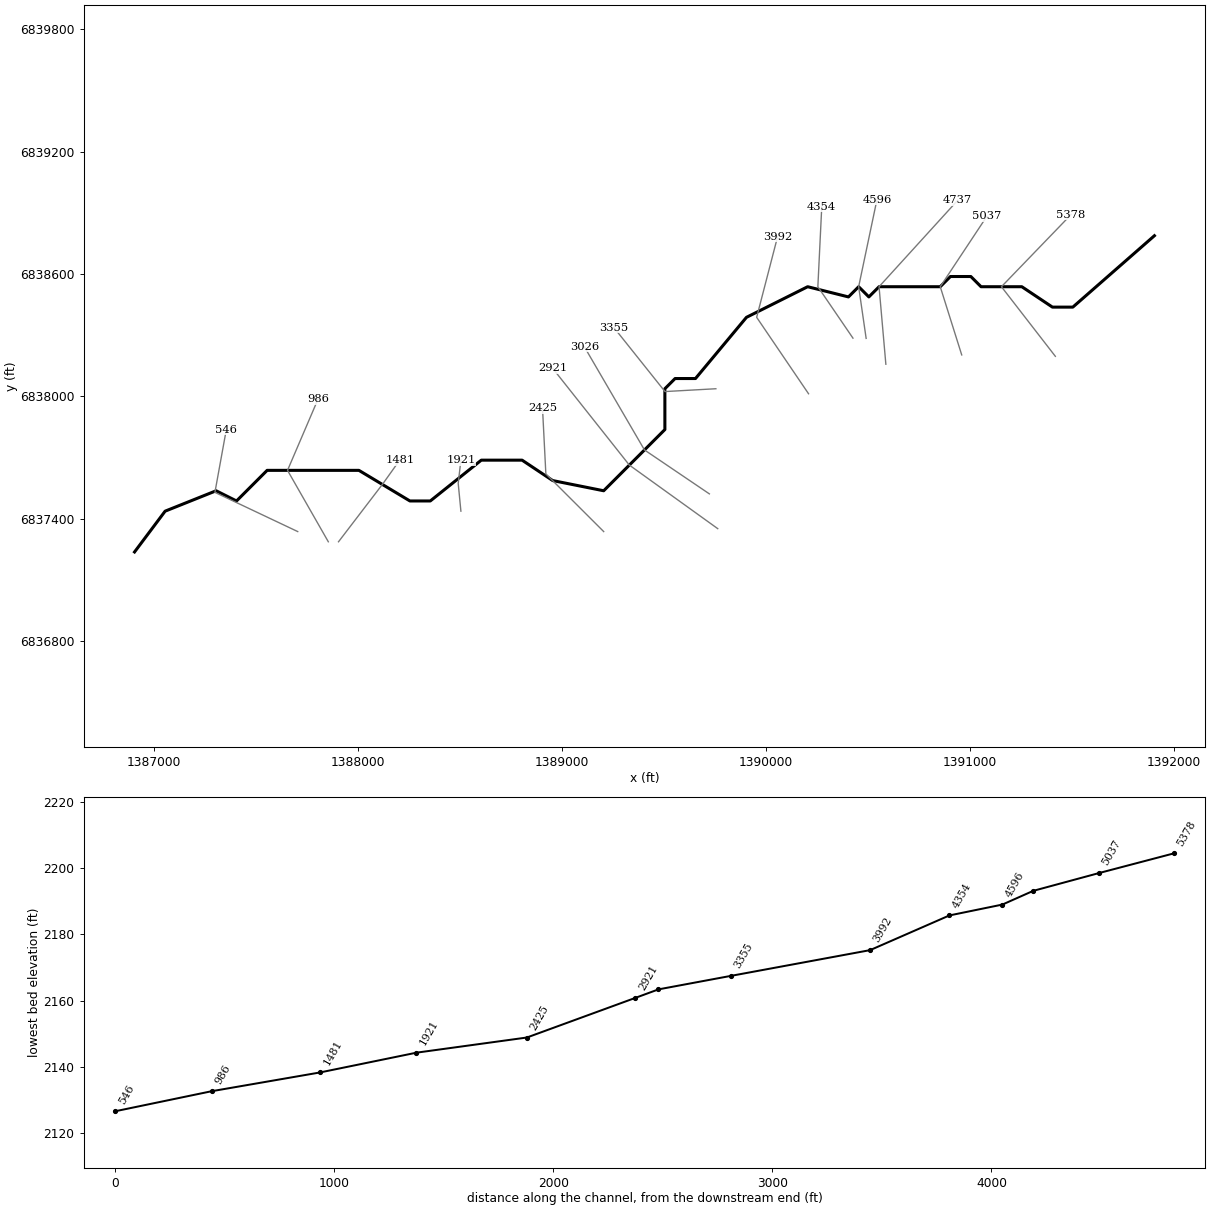
--- Sweetwater Creek Trib 20T5_1.prj (project) ---

Proj Title=Sweetwater Creek Trib 20T5_1 Base Level Engineering
Current Plan=p01
Default Exp/Contr=0.3,0.1
English Units
Geom File=g01
Flow File=f01
Plan File=p01
BEGIN DESCRIPTION:
Sweetwater Creek Trib 20T5_1
END DESCRIPTION:

--- Sweetwater Creek Trib 20T5_1.p01 (plan) ---

Plan Title=Multiple Run
Short Identifier=Multiple
Geom File=g01
Flow File=f01
Subcritical Flow
K Sum by GR= 0
Std Step Tol= 0.01
Critical Tol= 0.01
Num of Std Step Trials= 20
Max Error Tol= 0.3
Flow Tol Ratio= 0.001
Split Flow NTrial= 30
Split Flow Tol= 0.02
Split Flow Ratio= 0.02
Log Output Level= 0
Friction Slope Method= 1
Unsteady Friction Slope Method= 2
Unsteady Bridges Friction Slope Method= 1
Parabolic Critical Depth
Global Vel Dist=  1 , 1 , 1
Global Log Level= 0
CheckData=True
Encroach Param= -1, 0, 0, 0
BEGIN DESCRIPTION:
Multiple Run
END DESCRIPTION:

--- Sweetwater Creek Trib 20T5_1.f01 (steady flow) ---

Flow Title=Multiple
Number of Profiles=7
Profile Names=10-year,25-year,50-year,1pct_min,100-year,1pct_plu,500-year
River Rch & RM= Sweetwater Creek,Reach-1,5378
     340     492     621     391     781    1558    1247
Boundary for River Rch & Prof#=Sweetwater Creek,Reach-1,1
Up Type=0
Dn Type=3
Dn Slope=0.005
Boundary for River Rch & Prof#=Sweetwater Creek,Reach-1,2
Up Type=0
Dn Type=3
Dn Slope=0.005
Boundary for River Rch & Prof#=Sweetwater Creek,Reach-1,3
Up Type=0
Dn Type=3
Dn Slope=0.005
Boundary for River Rch & Prof#=Sweetwater Creek,Reach-1,4
Up Type=0
Dn Type=3
Dn Slope=0.005
Boundary for River Rch & Prof#=Sweetwater Creek,Reach-1,5
Up Type=0
Dn Type=3
Dn Slope=0.005
Boundary for River Rch & Prof#=Sweetwater Creek,Reach-1,6
Up Type=0
Dn Type=3
Dn Slope=0.005
Boundary for River Rch & Prof#=Sweetwater Creek,Reach-1,7
Up Type=0
Dn Type=3
Dn Slope=0.005

--- Sweetwater Creek Trib 20T5_1.g01 (geometry) ---

Geom Title=Existing Conditions

River Reach=Sweetwater Creek,Reach-1
Reach XY= 30
      1391905.00      6838788.00      1391505.00      6838438.00
      1391405.00      6838438.00      1391255.00      6838538.00
      1391055.00      6838538.00      1391005.00      6838588.00
      1390905.00      6838588.00      1390855.00      6838538.00
      1390555.00      6838538.00      1390505.00      6838488.00
      1390455.00      6838538.00      1390405.00      6838488.00
      1390205.00      6838538.00      1389905.00      6838388.00
      1389655.00      6838088.00      1389555.00      6838088.00
      1389505.00      6838038.00      1389505.00      6837838.00
      1389205.00      6837538.00      1388955.00      6837588.00
      1388805.00      6837688.00      1388605.00      6837688.00
      1388355.00      6837488.00      1388255.00      6837488.00
      1388005.00      6837638.00      1387555.00      6837638.00
      1387405.00      6837488.00      1387305.00      6837538.00
      1387055.00      6837438.00      1386905.00      6837238.00

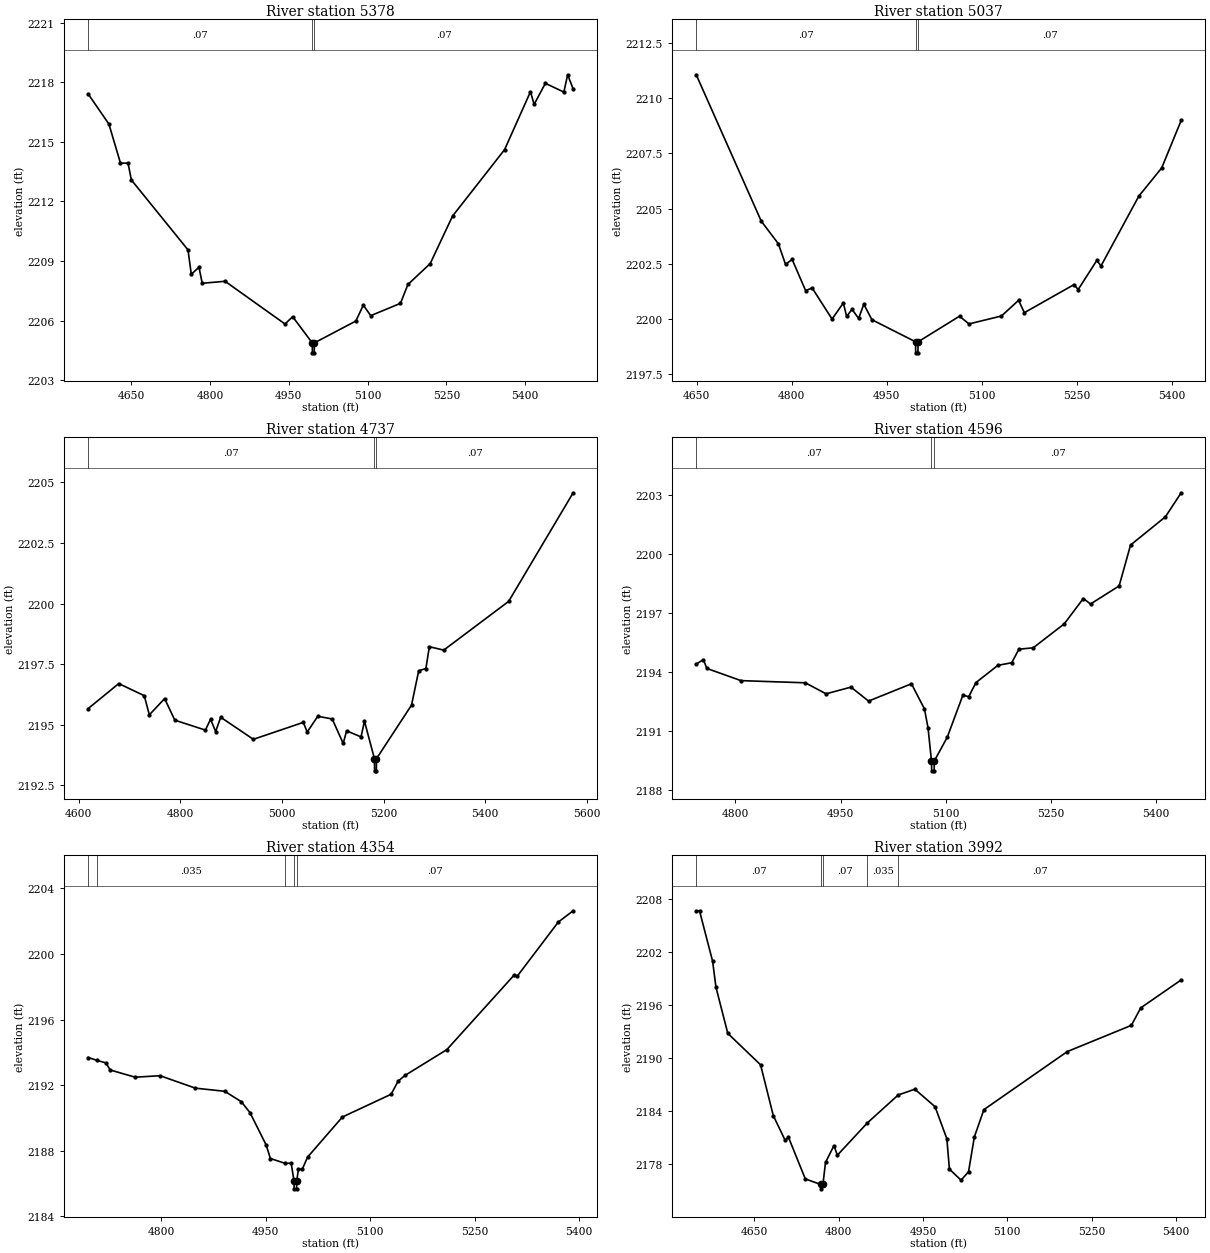
Type RM Length L Ch R = 1,5378,341,341,341
BEGIN DESCRIPTION:
Sweetwater Creek Trib 20T5_1 4107
END DESCRIPTION:
XS GIS Cut Line= 3
      1391419.34      6838196.82      1391155.00      6838538.00
      1391496.29      6838891.55
#Sta/Elev= 30
  4568.4 2217.40  4607.8 2215.89  4629.7 2213.93  4644.2 2213.92  4650.5 2213.08
  4758.3 2209.56  4764.6 2208.33  4779.1 2208.69  4785.4 2207.88  4828.9 2207.98
  4943.0 2205.83  4957.5 2206.20  4994.8 2204.88  4995.1 2204.38  4998.6 2204.38
  4998.8 2204.88  5077.8 2205.98  5092.0 2206.78  5106.1 2206.25  5162.7 2206.87
  5176.9 2207.82  5219.3 2208.87  5261.8 2211.26  5360.8 2214.60  5410.2 2217.52
  5417.1 2216.88  5438.5 2217.94  5473.7 2217.50  5480.9 2218.37  5491.4 2217.66
#Mann=3,-1,0
  4568.4    0.07       0  4994.8    0.07       0  4998.8    0.07       0
Bank Sta=4994.8,4998.8
Exp/Cntr=0.3,0.1

Type RM Length L Ch R = 1,5037,300,300,300
BEGIN DESCRIPTION:
Sweetwater Creek Trib 20T5_1 4148
END DESCRIPTION:
XS GIS Cut Line= 3
      1390960.29      6838203.69      1390855.00      6838538.00
      1391083.81      6838883.39
#Sta/Elev= 30
  4649.5 2211.06  4752.0 2204.43  4779.1 2203.40  4790.3 2202.47  4800.8 2202.69
  4822.0 2201.28  4832.3 2201.40  4863.7 2199.99  4881.5 2200.72  4886.7 2200.11
  4895.2 2200.43  4905.6 2200.02  4913.8 2200.66  4926.6 2199.96  4995.4 2198.96
  4995.6 2198.46  4999.1 2198.46  4999.4 2198.96  5064.7 2200.12  5079.7 2199.77
  5130.9 2200.13  5157.9 2200.84  5167.0 2200.28  5245.2 2201.55  5251.9 2201.33
  5281.3 2202.65  5287.9 2202.40  5347.5 2205.56  5383.6 2206.84  5414.3 2208.99
#Mann=3,-1,0
  4649.5    0.07       0  4995.4    0.07       0  4999.4    0.07       0
Bank Sta=4995.4,4999.4
Exp/Cntr=0.3,0.1

Type RM Length L Ch R = 1,4737,141,141,141
BEGIN DESCRIPTION:
Sweetwater Creek Trib 20T5_1 4106
END DESCRIPTION:
XS GIS Cut Line= 3
      1390588.36      6838158.16      1390555.00      6838538.00
      1390940.96      6838961.92
#Sta/Elev= 30
  4618.7 2195.67  4678.8 2196.70  4729.0 2196.20  4739.0 2195.41  4769.1 2196.08
  4789.2 2195.19  4849.4 2194.78  4859.5 2195.23  4869.5 2194.72  4879.5 2195.31
  4943.8 2194.40  5042.2 2195.10  5049.7 2194.70  5070.6 2195.35  5099.0 2195.24
  5120.6 2194.23  5127.4 2194.75  5155.7 2194.50  5162.5 2195.15  5182.1 2193.60
  5182.4 2193.10  5185.9 2193.10  5186.1 2193.60  5255.1 2195.81  5269.3 2197.23
  5283.4 2197.32  5290.2 2198.22  5318.6 2198.08  5446.3 2200.09  5573.3 2204.57
#Mann=3,-1,0
  4618.7    0.07       0  5182.1    0.07       0  5186.1    0.07       0
Bank Sta=5182.1,5186.1
Exp/Cntr=0.3,0.1

Type RM Length L Ch R = 1,4596,242,242,242
BEGIN DESCRIPTION:
Sweetwater Creek Trib 20T5_1 4147
END DESCRIPTION:
XS GIS Cut Line= 3
      1390491.71      6838284.75      1390455.00      6838538.00
      1390544.67      6838964.58
#Sta/Elev= 30
  4744.1 2194.39  4754.2 2194.62  4759.3 2194.17  4808.0 2193.55  4899.7 2193.44
  4929.3 2192.88  4964.9 2193.22  4989.9 2192.51  5051.1 2193.39  5069.7 2192.11
  5074.8 2191.14  5079.7 2189.46  5080.0 2188.96  5083.5 2188.96  5083.7 2189.46
  5102.2 2190.67  5124.6 2192.82  5132.8 2192.73  5143.1 2193.45  5174.5 2194.33
  5194.2 2194.46  5204.4 2195.15  5224.8 2195.22  5269.1 2196.44  5296.3 2197.73
  5306.6 2197.45  5347.4 2198.37  5363.7 2200.45  5413.5 2201.89  5435.9 2203.11
#Mann=3,-1,0
  4744.1    0.07       0  5079.7    0.07       0  5083.7    0.07       0
Bank Sta=5079.7,5083.7
Exp/Cntr=0.3,0.1

Type RM Length L Ch R = 1,4354,362,362,362
BEGIN DESCRIPTION:
Sweetwater Creek Trib 20T5_1 4146
END DESCRIPTION:
XS GIS Cut Line= 3
      1390427.09      6838285.94      1390255.00      6838538.00
      1390274.07      6838929.34
#Sta/Elev= 30
  4694.8 2193.69  4707.9 2193.51  4720.3 2193.36  4726.3 2192.93  4762.2 2192.49
  4798.1 2192.58  4848.9 2191.82  4891.0 2191.63  4914.7 2191.00  4927.3 2190.33
  4950.6 2188.35  4956.6 2187.53  4978.2 2187.23  4986.5 2187.25  4990.5 2186.18
  4990.8 2185.68  4994.3 2185.68  4994.5 2186.18  4997.0 2186.88  5002.5 2186.88
  5010.0 2187.61  5060.1 2190.06  5130.2 2191.45  5140.2 2192.25  5150.2 2192.60
  5210.2 2194.17  5306.8 2198.71  5311.8 2198.67  5370.4 2201.95  5391.8 2202.64
#Mann=5,-1,0
  4694.8    0.07       0  4707.9   0.035       0  4978.2    0.07       0
  4990.5    0.07       0  4994.5    0.07       0
Bank Sta=4990.5,4994.5
Exp/Cntr=0.3,0.1

Type RM Length L Ch R = 1,3992,637,637,637
BEGIN DESCRIPTION:
Sweetwater Creek Trib 20T5_1 4105
END DESCRIPTION:
XS GIS Cut Line= 3
      1390209.37      6838013.40      1389955.00      6838388.00
      1390057.71      6838783.69
#Sta/Elev= 30
  4547.2 2206.67  4553.0 2206.67  4576.3 2200.96  4582.3 2198.00  4603.3 2192.80
  4661.5 2189.25  4684.1 2183.50  4705.1 2180.72  4711.1 2181.05  4741.0 2176.34
  4768.3 2175.72  4768.6 2175.22  4772.3 2175.72  4776.9 2178.21  4791.9 2180.11
  4797.9 2179.02  4851.3 2182.68  4905.9 2185.83  4935.6 2186.49  4971.5 2184.51
  4992.5 2180.88  4997.0 2177.45  5017.7 2176.20  5031.0 2177.15  5041.3 2181.08
  5058.3 2184.18  5206.6 2190.75  5320.3 2193.71  5337.0 2195.69  5408.8 2198.85
#Mann=5,-1,0
  4547.2    0.07       0  4768.3    0.07       0  4772.3    0.07       0
  4851.3   0.035       0  4905.9    0.07       0
Bank Sta=4768.3,4772.3
Exp/Cntr=0.3,0.1

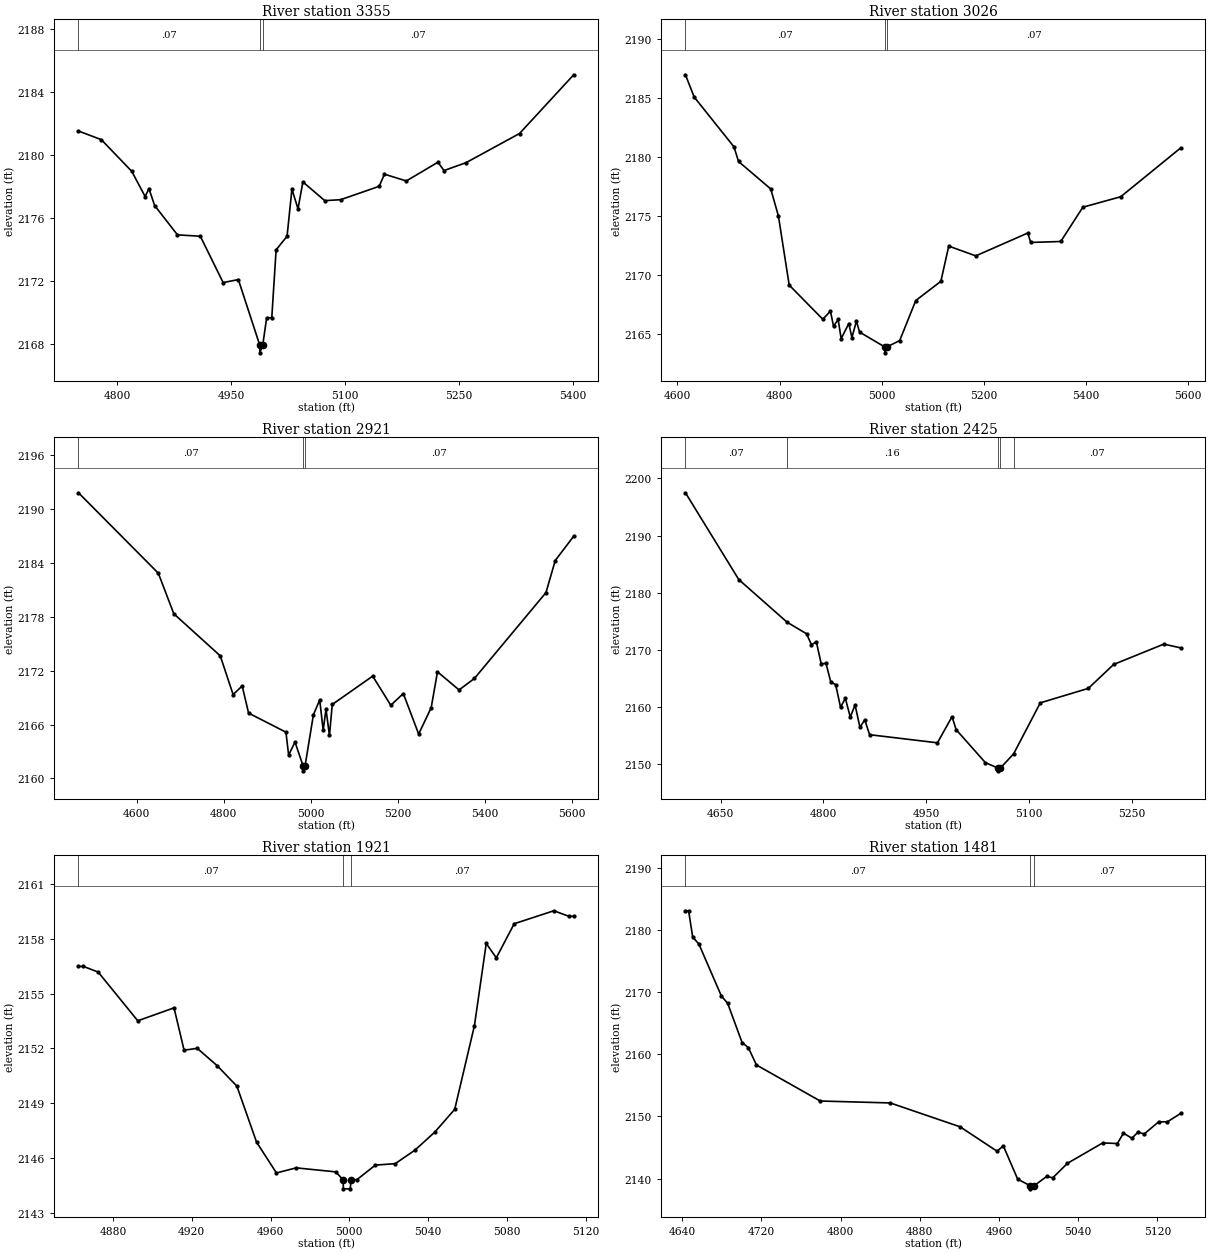
Type RM Length L Ch R = 1,3355,329,329,329
BEGIN DESCRIPTION:
Sweetwater Creek Trib 20T5_1 6.0
END DESCRIPTION:
XS GIS Cut Line= 3
      1389755.02      6838038.00      1389505.50      6838024.16
      1389254.97      6838338.03
#Sta/Elev= 30
  4749.3 2181.52  4779.4 2180.97  4819.4 2178.96  4837.0 2177.36  4842.0 2177.86
  4849.5 2176.79  4879.5 2174.93  4909.6 2174.84  4939.6 2171.90  4959.6 2172.09
  4987.7 2167.94  4987.9 2167.44  4991.7 2167.94  4996.9 2169.67  5003.6 2169.67
  5009.3 2173.98  5023.7 2174.84  5030.1 2177.83  5038.1 2176.58  5044.5 2178.29
  5073.3 2177.10  5094.1 2177.16  5144.9 2178.01  5151.8 2178.78  5180.6 2178.35
  5222.2 2179.54  5230.2 2179.01  5259.1 2179.51  5329.5 2181.36  5400.8 2185.09
#Mann=3,-1,0
  4749.3    0.07       0  4987.7    0.07       0  4991.7    0.07       0
Bank Sta=4987.7,4991.7
Exp/Cntr=0.3,0.1

Type RM Length L Ch R = 1,3026,105,105,105
BEGIN DESCRIPTION:
Sweetwater Creek Trib 20T5_1 5.1
END DESCRIPTION:
XS GIS Cut Line= 3
      1389723.12      6837522.75      1389405.00      6837738.00
      1389110.46      6838243.32
#Sta/Elev= 30
  4615.9 2186.99  4633.0 2185.10  4710.9 2180.87  4719.8 2179.63  4782.8 2177.30
  4797.8 2175.01  4818.9 2169.14  4884.7 2166.24  4899.6 2166.93  4905.7 2165.64
  4914.6 2166.22  4920.6 2164.60  4935.6 2165.88  4941.6 2164.69  4950.5 2166.08
  4956.6 2165.15  5005.9 2163.89  5006.1 2163.39  5009.9 2163.89  5035.1 2164.43
  5066.6 2167.83  5115.7 2169.46  5131.1 2172.45  5184.0 2171.62  5285.8 2173.56
  5291.5 2172.76  5350.3 2172.84  5393.5 2175.75  5467.7 2176.64  5584.9 2180.78
#Mann=3,-1,0
  4615.9    0.07       0  5005.9    0.07       0  5009.9    0.07       0
Bank Sta=5005.9,5009.9
Exp/Cntr=0.3,0.1

Type RM Length L Ch R = 1,2921,496,496,496
BEGIN DESCRIPTION:
Sweetwater Creek Trib 20T5_1 5.0
END DESCRIPTION:
XS GIS Cut Line= 3
      1389764.17      6837352.30      1389330.84      6837663.84
      1388955.03      6838137.96
#Sta/Elev= 30
  4466.3 2191.84  4649.9 2182.87  4685.5 2178.35  4792.3 2173.66  4821.8 2169.35
  4842.7 2170.30  4857.4 2167.28  4943.3 2165.15  4949.5 2162.60  4964.2 2164.05
  4983.1 2161.34  4983.3 2160.84  4987.1 2161.34  5006.5 2167.09  5021.0 2168.74
  5029.0 2165.36  5035.4 2167.72  5043.4 2164.78  5049.8 2168.24  5142.8 2171.40
  5184.4 2168.15  5213.2 2169.46  5248.5 2164.94  5277.3 2167.88  5291.8 2171.88
  5341.4 2169.86  5376.7 2171.14  5541.2 2180.71  5562.6 2184.29  5605.0 2187.00
#Mann=3,-1,0
  4466.3    0.07       0  4983.1    0.07       0  4987.1    0.07       0
Bank Sta=4983.1,4987.1
Exp/Cntr=0.3,0.1

Type RM Length L Ch R = 1,2425,504,504,504
BEGIN DESCRIPTION:
Sweetwater Creek Trib 20T5_1 4.0
END DESCRIPTION:
XS GIS Cut Line= 3
      1389205.03      6837337.97      1388921.49      6837620.90
      1388905.13      6837942.53
#Sta/Elev= 30
  4598.8 2197.49  4676.6 2182.32  4747.1 2174.86  4775.6 2172.83  4782.7 2170.90
  4789.8 2171.44  4796.8 2167.62  4803.9 2167.65  4811.0 2164.35  4818.0 2163.95
  4825.1 2160.00  4832.2 2161.54  4839.3 2158.27  4846.3 2160.39  4853.4 2156.50
  4860.5 2157.78  4867.5 2155.19  4966.5 2153.77  4987.8 2158.34  4993.8 2156.07
  5036.5 2150.30  5054.5 2149.37  5054.8 2148.87  5058.5 2149.37  5077.7 2151.85
  5116.6 2160.76  5186.7 2163.29  5223.6 2167.47  5296.8 2171.03  5321.4 2170.37
#Mann=5,-1,0
  4598.8    0.07       0  4747.1    0.16       0  5054.5    0.07       0
  5058.5    0.16       0  5077.7    0.07       0
Bank Sta=5054.5,5058.5
Exp/Cntr=0.3,0.1

Type RM Length L Ch R = 1,1921,440,440,440
BEGIN DESCRIPTION:
Sweetwater Creek Trib 20T5_1 3.0
END DESCRIPTION:
XS GIS Cut Line= 3
      1388505.00      6837438.02      1388491.81      6837574.32
      1388505.00      6837688.02
#Sta/Elev= 30
  4862.5 2156.49  4865.0 2156.49  4872.5 2156.18  4892.6 2153.51  4911.0 2154.22
  4916.1 2151.90  4922.8 2152.00  4932.8 2151.06  4942.9 2149.93  4952.9 2146.86
  4963.0 2145.17  4973.0 2145.45  4993.1 2145.23  4996.8 2144.80  4997.0 2144.30
  5000.5 2144.30  5000.8 2144.80  5003.8 2144.80  5013.2 2145.60  5023.3 2145.68
  5033.3 2146.42  5043.4 2147.41  5053.5 2148.66  5063.5 2153.24  5069.5 2157.75
  5074.6 2156.96  5083.7 2158.83  5103.8 2159.54  5111.4 2159.24  5113.9 2159.24
#Mann=3,-1,0
  4862.5    0.07       0  4996.8    0.07       0  5000.8    0.07       0
Bank Sta=4996.8,5000.8
Exp/Cntr=0.3,0.1

Type RM Length L Ch R = 1,1481,495,495,495
BEGIN DESCRIPTION:
Sweetwater Creek Trib 20T5_1 2.0
END DESCRIPTION:
XS GIS Cut Line= 3
      1387904.98      6837287.98      1388121.52      6837570.98
      1388205.01      6837688.01
#Sta/Elev= 30
  4643.3 2183.14  4646.5 2183.14  4650.6 2178.91  4656.9 2177.77  4679.6 2169.40
  4685.9 2168.25  4700.5 2161.91  4706.8 2161.09  4715.0 2158.30  4779.4 2152.49
  4850.1 2152.18  4920.7 2148.33  4958.0 2144.40  4964.3 2145.27  4978.8 2139.91
  4991.4 2138.84  4991.6 2138.34  4995.4 2138.84  5008.2 2140.35  5014.3 2140.12
  5029.1 2142.45  5064.7 2145.74  5079.5 2145.64  5085.6 2147.31  5094.2 2146.49
  5100.4 2147.50  5106.5 2147.17  5121.3 2149.15  5129.9 2149.13  5143.4 2150.49
#Mann=3,-1,0
  4643.3    0.07       0  4991.4    0.07       0  4995.4    0.07       0
Bank Sta=4991.4,4995.4
Exp/Cntr=0.3,0.1

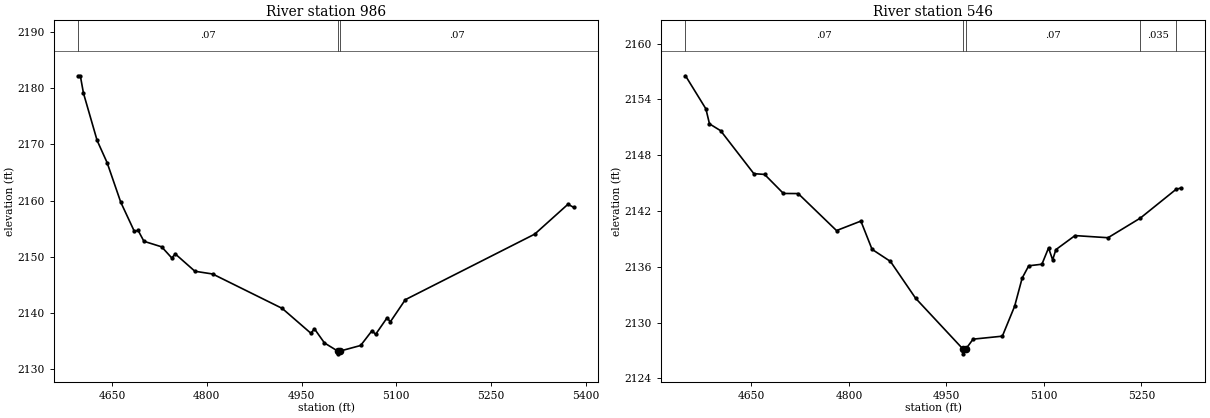
Type RM Length L Ch R = 1,986,440,440,440
BEGIN DESCRIPTION:
Sweetwater Creek Trib 20T5_1 1.0
END DESCRIPTION:
XS GIS Cut Line= 3
      1387855.00      6837288.01      1387654.97      6837638.08
      1387804.99      6837987.98
#Sta/Elev= 30
  4596.9 2182.24  4599.8 2182.24  4604.8 2179.13  4626.4 2170.71  4642.2 2166.76
  4663.8 2159.71  4685.4 2154.49  4691.2 2154.70  4700.5 2152.74  4728.6 2151.75
  4744.5 2149.78  4750.2 2150.48  4781.2 2147.40  4809.3 2146.91  4919.4 2140.78
  4964.7 2136.36  4970.5 2137.13  4986.3 2134.62  5007.2 2133.18  5007.4 2132.68
  5011.2 2133.18  5043.6 2134.17  5061.7 2136.82  5067.2 2136.14  5085.3 2139.08
  5090.7 2138.40  5114.3 2142.33  5319.2 2154.02  5371.8 2159.34  5380.8 2158.79
#Mann=3,-1,0
  4596.9    0.07       0  5007.2    0.07       0  5011.2    0.07       0
Bank Sta=5007.2,5011.2
Exp/Cntr=0.3,0.1

Type RM Length L Ch R = 1,546,0,0,0
BEGIN DESCRIPTION:
Sweetwater Creek Trib 20T5_1 2952
END DESCRIPTION:
XS GIS Cut Line= 3
      1387705.01      6837337.99      1387299.09      6837530.17
      1387355.00      6837838.01
#Sta/Elev= 30
  4548.5 2156.55  4579.9 2152.99  4585.4 2151.38  4602.6 2150.64  4653.7 2146.02
  4670.2 2145.94  4699.2 2143.89  4721.9 2143.88  4780.9 2139.90  4818.4 2140.92
  4835.6 2137.88  4863.9 2136.58  4902.6 2132.62  4975.7 2127.14  4975.9 2126.64
  4979.7 2127.14  4991.1 2128.22  5036.1 2128.54  5055.0 2131.76  5066.6 2134.79
  5076.7 2136.11  5097.0 2136.28  5107.2 2138.03  5113.5 2136.75  5118.5 2137.85
  5147.9 2139.36  5198.7 2139.13  5248.4 2141.24  5303.5 2144.34  5310.5 2144.47
#Mann=5,-1,0
  4548.5    0.07       0  4975.7    0.07       0  4979.7    0.07       0
  5248.4   0.035       0  5303.5    0.07       0
Bank Sta=4975.7,4979.7
Exp/Cntr=0.3,0.1

Chan Stop Cuts=-1