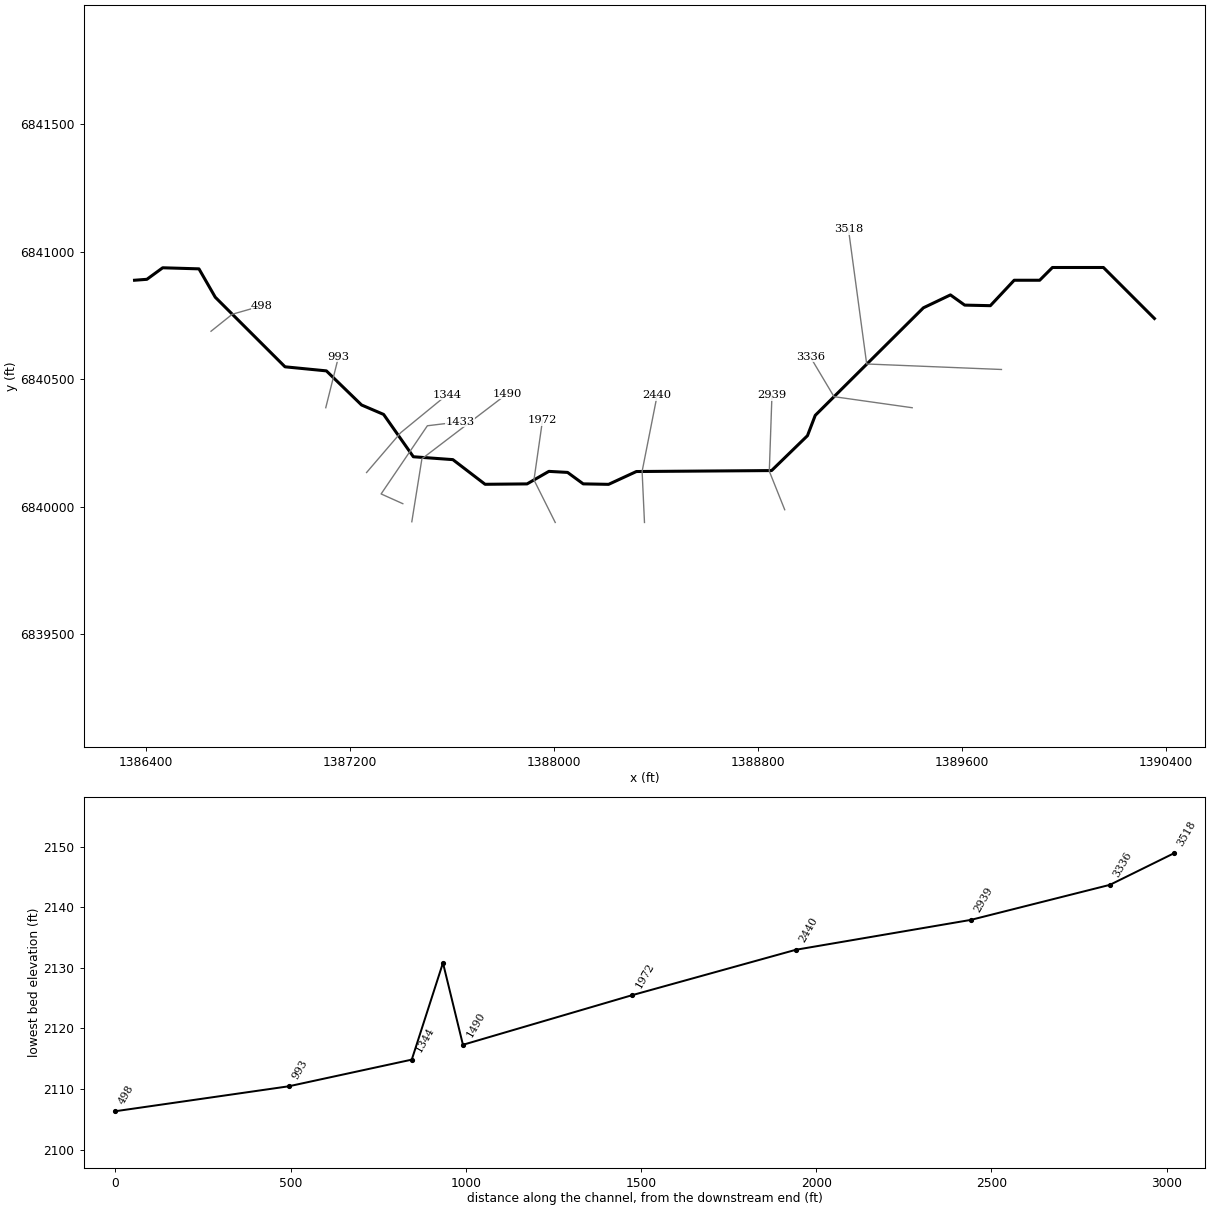
--- Sweetwater Creek Trib 20T6.prj (project) ---

Proj Title=Sweetwater Creek Trib 20T6 Base Level Engineering
Current Plan=p01
Default Exp/Contr=0.3,0.1
English Units
Geom File=g01
Flow File=f01
Plan File=p01
BEGIN DESCRIPTION:
Sweetwater Creek Trib 20T6
END DESCRIPTION:

--- Sweetwater Creek Trib 20T6.p01 (plan) ---

Plan Title=Multiple Run
Short Identifier=Multiple
Geom File=g01
Flow File=f01
Subcritical Flow
K Sum by GR= 0
Std Step Tol= 0.01
Critical Tol= 0.01
Num of Std Step Trials= 20
Max Error Tol= 0.3
Flow Tol Ratio= 0.001
Split Flow NTrial= 30
Split Flow Tol= 0.02
Split Flow Ratio= 0.02
Log Output Level= 0
Friction Slope Method= 1
Unsteady Friction Slope Method= 2
Unsteady Bridges Friction Slope Method= 1
Parabolic Critical Depth
Global Vel Dist=  1 , 1 , 1
Global Log Level= 0
CheckData=True
Encroach Param= -1, 0, 0, 0
BEGIN DESCRIPTION:
Multiple Run
END DESCRIPTION:

--- Sweetwater Creek Trib 20T6.f01 (steady flow) ---

Flow Title=Multiple
Number of Profiles=7
Profile Names=10-year,25-year,50-year,1pct_min,100-year,1pct_plu,500-year
River Rch & RM= Sweetwater Creek,Reach-1,3518
     153     210     257     157     313     625     471
Boundary for River Rch & Prof#=Sweetwater Creek,Reach-1,1
Up Type=0
Dn Type=3
Dn Slope=0.005
Boundary for River Rch & Prof#=Sweetwater Creek,Reach-1,2
Up Type=0
Dn Type=3
Dn Slope=0.005
Boundary for River Rch & Prof#=Sweetwater Creek,Reach-1,3
Up Type=0
Dn Type=3
Dn Slope=0.005
Boundary for River Rch & Prof#=Sweetwater Creek,Reach-1,4
Up Type=0
Dn Type=3
Dn Slope=0.005
Boundary for River Rch & Prof#=Sweetwater Creek,Reach-1,5
Up Type=0
Dn Type=3
Dn Slope=0.005
Boundary for River Rch & Prof#=Sweetwater Creek,Reach-1,6
Up Type=0
Dn Type=3
Dn Slope=0.005
Boundary for River Rch & Prof#=Sweetwater Creek,Reach-1,7
Up Type=0
Dn Type=3
Dn Slope=0.005

--- Sweetwater Creek Trib 20T6.g01 (geometry) ---

Geom Title=Existing Conditions

River Reach=Sweetwater Creek,Reach-1
Reach XY= 30
      1390355.00      6840738.00      1390155.00      6840938.00
      1389955.00      6840938.00      1389905.00      6840888.00
      1389805.00      6840888.00      1389711.55      6840788.24
      1389610.86      6840790.46      1389554.99      6840830.47
      1389448.95      6840779.88      1389024.79      6840358.09
      1388994.22      6840278.32      1388853.54      6840141.54
      1388323.27      6840137.79      1388214.26      6840087.50
      1388114.67      6840089.37      1388053.40      6840134.29
      1387980.00      6840138.40      1387894.50      6840089.22
      1387729.88      6840087.71      1387603.53      6840184.44
      1387448.53      6840195.70      1387331.88      6840361.73
      1387245.32      6840398.78      1387107.45      6840532.53
      1386945.20      6840548.48      1386671.66      6840821.34
      1386607.70      6840932.65      1386465.47      6840936.90
      1386403.49      6840891.65      1386355.00      6840888.00

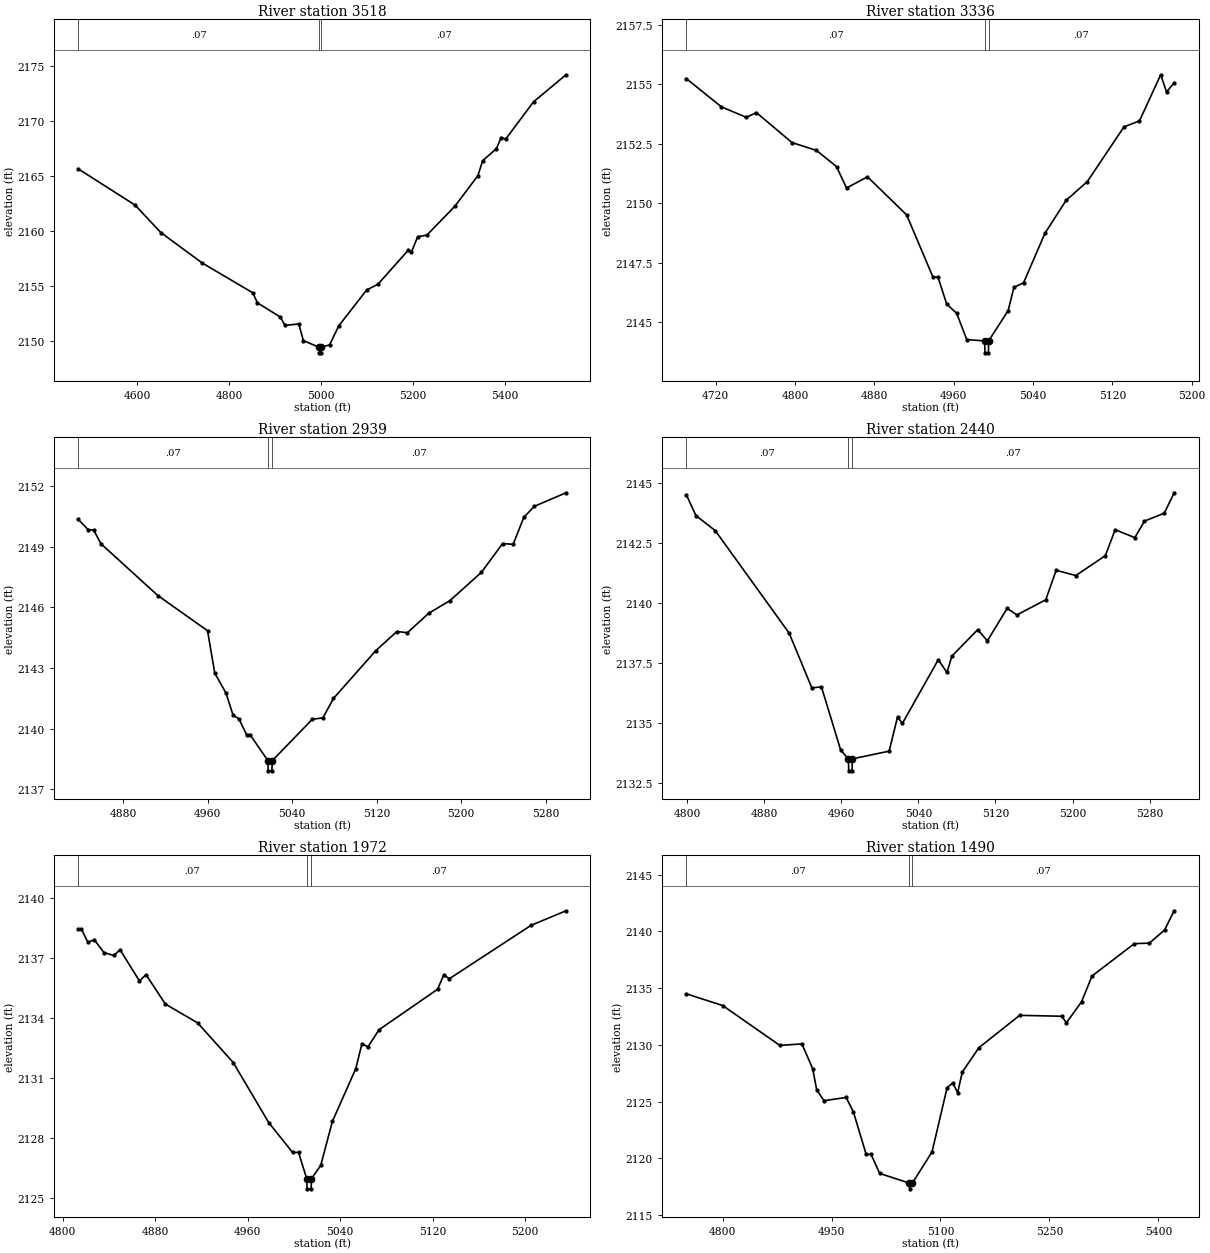
Type RM Length L Ch R = 1,3518,182,182,182
BEGIN DESCRIPTION:
Sweetwater Creek Trib 20T6 7.0
END DESCRIPTION:
XS GIS Cut Line= 3
      1389754.99      6840538.00      1389226.53      6840559.55
      1389155.00      6841088.03
#Sta/Elev= 30
  4471.1 2165.64  4595.0 2162.34  4651.2 2159.84  4741.3 2157.07  4851.4 2154.36
  4861.4 2153.45  4911.5 2152.15  4921.5 2151.39  4951.5 2151.53  4961.5 2150.01
  4996.3 2149.40  4996.5 2148.90  5000.0 2148.90  5000.3 2149.40  5018.6 2149.63
  5038.8 2151.37  5099.4 2154.62  5123.9 2155.14  5190.2 2158.25  5196.5 2158.04
  5210.4 2159.46  5230.5 2159.61  5291.1 2162.22  5341.5 2165.02  5351.8 2166.37
  5381.9 2167.48  5392.0 2168.48  5402.1 2168.35  5462.6 2171.73  5533.3 2174.19
#Mann=3,-1,0
  4471.1    0.07       0  4996.3    0.07       0  5000.3    0.07       0
Bank Sta=4996.3,5000.3
Exp/Cntr=0.3,0.1

Type RM Length L Ch R = 1,3336,397,397,397
BEGIN DESCRIPTION:
Sweetwater Creek Trib 20T6 6.0
END DESCRIPTION:
XS GIS Cut Line= 3
      1389404.97      6840388.00      1389098.32      6840431.34
      1389005.02      6840587.96
#Sta/Elev= 30
  4690.3 2155.24  4725.8 2154.05  4750.9 2153.61  4761.0 2153.81  4796.9 2152.55
  4821.6 2152.22  4841.8 2151.54  4851.9 2150.64  4873.0 2151.11  4912.5 2149.51
  4939.1 2146.89  4944.1 2146.90  4952.9 2145.76  4963.0 2145.37  4973.1 2144.27
  4991.2 2144.21  4991.5 2143.71  4995.0 2143.71  4995.2 2144.21  5014.9 2145.49
  5020.7 2146.46  5030.5 2146.66  5051.9 2148.73  5073.3 2150.12  5094.7 2150.91
  5131.7 2153.21  5147.3 2153.46  5168.7 2155.40  5174.6 2154.68  5182.3 2155.06
#Mann=3,-1,0
  4690.3    0.07       0  4991.2    0.07       0  4995.2    0.07       0
Bank Sta=4991.2,4995.2
Exp/Cntr=0.3,0.1

Type RM Length L Ch R = 1,2939,499,499,499
BEGIN DESCRIPTION:
Sweetwater Creek Trib 20T6 5.0
END DESCRIPTION:
XS GIS Cut Line= 3
      1388905.00      6839987.99      1388844.57      6840139.05
      1388855.00      6840437.97
#Sta/Elev= 30
  4837.3 2150.36  4846.7 2149.85  4852.1 2149.82  4858.9 2149.15  4912.7 2146.59
  4959.8 2144.85  4966.6 2142.76  4977.3 2141.76  4984.0 2140.67  4989.4 2140.50
  4996.7 2139.71  5000.0 2139.71  5017.0 2138.42  5017.2 2137.92  5020.7 2137.92
  5021.0 2138.42  5059.0 2140.47  5069.0 2140.54  5079.0 2141.50  5119.0 2143.86
  5139.0 2144.81  5149.0 2144.75  5169.1 2145.71  5189.1 2146.33  5219.1 2147.74
  5239.1 2149.16  5249.1 2149.12  5259.1 2150.45  5269.1 2151.00  5299.1 2151.67
#Mann=3,-1,0
  4837.3    0.07       0  5017.0    0.07       0  5021.0    0.07       0
Bank Sta=5017,5021
Exp/Cntr=0.3,0.1

Type RM Length L Ch R = 1,2440,468,468,468
BEGIN DESCRIPTION:
Sweetwater Creek Trib 20T6 4.0
END DESCRIPTION:
XS GIS Cut Line= 3
      1388355.00      6839937.97      1388345.72      6840138.45
      1388405.01      6840438.04
#Sta/Elev= 30
  4799.3 2144.50  4809.3 2143.63  4829.4 2143.00  4906.0 2138.73  4929.5 2136.45
  4939.5 2136.49  4959.5 2133.85  4967.5 2133.49  4967.8 2132.99  4971.3 2132.99
  4971.5 2133.49  5009.7 2133.81  5018.4 2135.23  5023.5 2134.97  5060.7 2137.62
  5069.7 2137.09  5074.8 2137.77  5101.5 2138.87  5111.7 2138.41  5132.1 2139.76
  5142.3 2139.49  5172.2 2140.12  5183.0 2141.35  5203.4 2141.13  5234.0 2141.96
  5244.2 2143.04  5264.6 2142.71  5274.6 2143.40  5295.2 2143.73  5305.4 2144.58
#Mann=3,-1,0
  4799.3    0.07       0  4967.5    0.07       0  4971.5    0.07       0
Bank Sta=4967.5,4971.5
Exp/Cntr=0.3,0.1

Type RM Length L Ch R = 1,1972,482,482,482
BEGIN DESCRIPTION:
Sweetwater Creek Trib 20T6 3.0
END DESCRIPTION:
XS GIS Cut Line= 3
      1388005.00      6839937.99      1387921.58      6840104.90
      1387955.00      6840338.02
#Sta/Elev= 30
  4813.4 2138.46  4816.2 2138.46  4821.8 2137.80  4827.4 2137.92  4835.8 2137.28
  4844.2 2137.14  4849.7 2137.42  4866.5 2135.86  4872.1 2136.18  4888.9 2134.71
  4916.8 2133.77  4947.6 2131.79  4978.3 2128.79  4998.9 2127.30  5004.1 2127.30
  5011.2 2125.98  5011.5 2125.48  5015.0 2125.48  5015.2 2125.98  5023.3 2126.65
  5033.4 2128.85  5053.6 2131.48  5059.0 2132.74  5064.1 2132.57  5073.8 2133.43
  5124.4 2135.45  5129.6 2136.15  5134.7 2135.98  5205.2 2138.64  5235.5 2139.37
#Mann=3,-1,0
  4813.4    0.07       0  5011.2    0.07       0  5015.2    0.07       0
Bank Sta=5011.2,5015.2
Exp/Cntr=0.3,0.1

Type RM Length L Ch R = 1,1490,57,57,57
BEGIN DESCRIPTION:
Sweetwater Creek Trib 20T6 2.0
END DESCRIPTION:
XS GIS Cut Line= 3
      1387442.48      6839940.78      1387482.05      6840187.63
      1387817.42      6840443.45
#Sta/Elev= 30
  4750.0 2134.50  4800.2 2133.46  4878.8 2129.95  4909.2 2130.08  4924.1 2127.89
  4929.5 2126.05  4939.6 2125.07  4970.0 2125.36  4980.1 2124.09  4997.7 2120.34
  5004.4 2120.34  5016.3 2118.66  5057.3 2117.80  5057.6 2117.30  5061.3 2117.80
  5088.4 2120.56  5109.2 2126.23  5116.9 2126.63  5123.7 2125.78  5130.0 2127.59
  5152.8 2129.74  5209.0 2132.60  5267.1 2132.52  5273.4 2131.94  5294.2 2133.79
  5308.7 2136.07  5366.9 2138.92  5387.7 2138.97  5408.5 2140.12  5421.8 2141.82
#Mann=3,-1,0
  4750.0    0.07       0  5057.3    0.07       0  5061.3    0.07       0
Bank Sta=5057.3,5061.3
Exp/Cntr=0.3,0.1

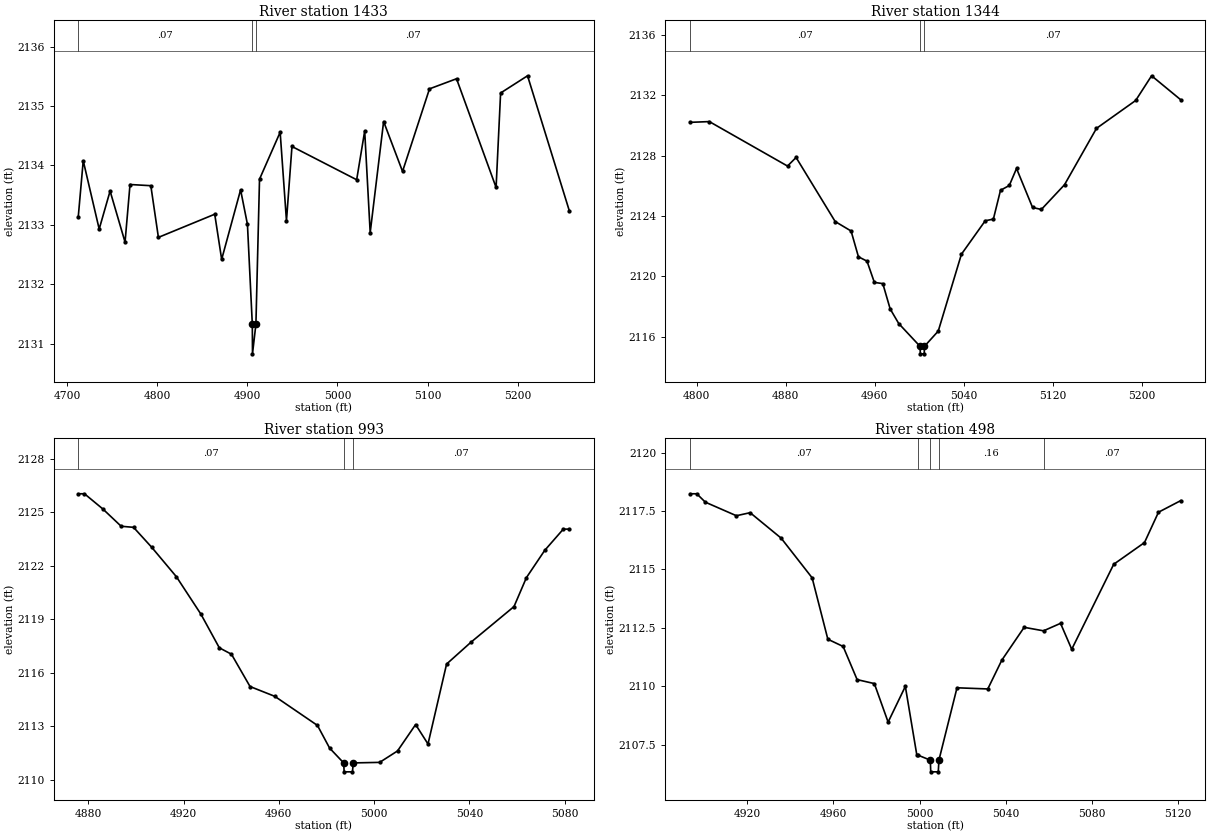
Type RM Length L Ch R = 1,1433,89,89,89
BEGIN DESCRIPTION:
Sweetwater Creek Trib 20T6 4148
END DESCRIPTION:
XS GIS Cut Line= 5
      1387407.18      6840011.68      1387322.07      6840049.89
      1387432.31      6840212.22      1387503.50      6840317.26
      1387630.96      6840332.76
#Sta/Elev= 30
  4712.4 2133.14  4717.9 2134.08  4735.6 2132.93  4747.7 2133.57  4764.3 2132.71
  4769.8 2133.68  4792.9 2133.66  4801.3 2132.79  4863.8 2133.18  4871.5 2132.42
  4892.5 2133.59  4900.1 2133.01  4905.5 2131.33  4905.7 2130.83  4909.5 2131.33
  4913.5 2133.77  4936.4 2134.56  4943.4 2133.07  4949.5 2134.32  5021.3 2133.76
  5030.2 2134.58  5036.3 2132.87  5051.2 2134.74  5072.2 2133.90  5102.1 2135.29
  5132.1 2135.46  5176.0 2133.63  5181.0 2135.22  5210.9 2135.51  5257.2 2133.24
#Mann=3,-1,0
  4712.4    0.07       0  4905.5    0.07       0  4909.5    0.07       0
Bank Sta=4905.5,4909.5
Exp/Cntr=0.3,0.1

Type RM Length L Ch R = 1,1344,351,351,351
BEGIN DESCRIPTION:
Sweetwater Creek Trib 20T6 4062
END DESCRIPTION:
XS GIS Cut Line= 3
      1387265.06      6840133.88      1387399.14      6840290.28
      1387580.99      6840439.12
#Sta/Elev= 30
  4794.0 2130.21  4811.5 2130.26  4881.7 2127.31  4889.4 2127.88  4924.5 2123.63
  4938.8 2123.00  4945.4 2121.29  4953.1 2121.00  4959.7 2119.59  4967.3 2119.51
  4973.9 2117.83  4981.6 2116.86  5000.7 2115.35  5001.0 2114.85  5004.5 2114.85
  5004.7 2115.35  5017.1 2116.36  5037.9 2121.46  5059.3 2123.68  5066.6 2123.79
  5073.0 2125.70  5080.9 2126.02  5087.4 2127.15  5101.8 2124.56  5109.7 2124.43
  5130.5 2126.07  5159.2 2129.81  5194.4 2131.66  5208.7 2133.30  5235.0 2131.70
#Mann=3,-1,0
  4794.0    0.07       0  5000.7    0.07       0  5004.7    0.07       0
Bank Sta=5000.7,5004.7
Exp/Cntr=0.3,0.1

Type RM Length L Ch R = 1,993,495,495,495
BEGIN DESCRIPTION:
Sweetwater Creek Trib 20T6 1.0
END DESCRIPTION:
XS GIS Cut Line= 3
      1387105.00      6840388.02      1387135.20      6840508.49
      1387154.99      6840587.96
#Sta/Elev= 29
  4875.8 2126.03  4878.4 2126.03  4886.1 2125.18  4893.8 2124.21  4899.0 2124.15
  4906.7 2123.02  4917.0 2121.38  4927.3 2119.28  4935.0 2117.40  4940.1 2117.04
  4947.9 2115.23  4958.3 2114.68  4976.2 2113.05  4981.3 2111.78  4987.2 2110.95
  4987.4 2110.45  4990.9 2110.45  4991.2 2110.95  5002.3 2110.98  5009.8 2111.62
  5017.4 2113.10  5022.6 2112.01  5030.4 2116.49  5040.7 2117.72  5058.7 2119.71
  5063.9 2121.33  5071.6 2122.86  5079.4 2124.05  5081.9 2124.05
#Mann=3,-1,0
  4875.8    0.07       0  4987.2    0.07       0  4991.2    0.07       0
Bank Sta=4987.2,4991.2
Exp/Cntr=0.3,0.1

Type RM Length L Ch R = 1,498,0,0,0
BEGIN DESCRIPTION:
Sweetwater Creek Trib 20T6 1704
END DESCRIPTION:
XS GIS Cut Line= 3
      1386654.99      6840687.99      1386738.30      6840754.65
      1386855.03      6840788.01
#Sta/Elev= 30
  4893.3 2118.24  4896.5 2118.24  4900.5 2117.88  4914.9 2117.30  4921.3 2117.43
  4935.7 2116.34  4950.1 2114.64  4957.4 2112.01  4964.5 2111.70  4971.0 2110.28
  4979.0 2110.11  4985.4 2108.46  4993.4 2109.99  4998.7 2107.07  4999.4 2107.04
  5005.0 2106.83  5005.2 2106.33  5008.7 2106.33  5009.0 2106.83  5017.4 2109.93
  5031.7 2109.88  5038.2 2111.11  5048.6 2112.52  5057.6 2112.37  5065.5 2112.69
  5070.7 2111.58  5090.2 2115.22  5104.5 2116.15  5111.0 2117.45  5121.4 2117.95
#Mann=5,-1,0
  4893.3    0.07       0  4999.4    0.16       0  5005.0    0.07       0
  5009.0    0.16       0  5057.6    0.07       0
Bank Sta=5005,5009
Exp/Cntr=0.3,0.1

Chan Stop Cuts=-1