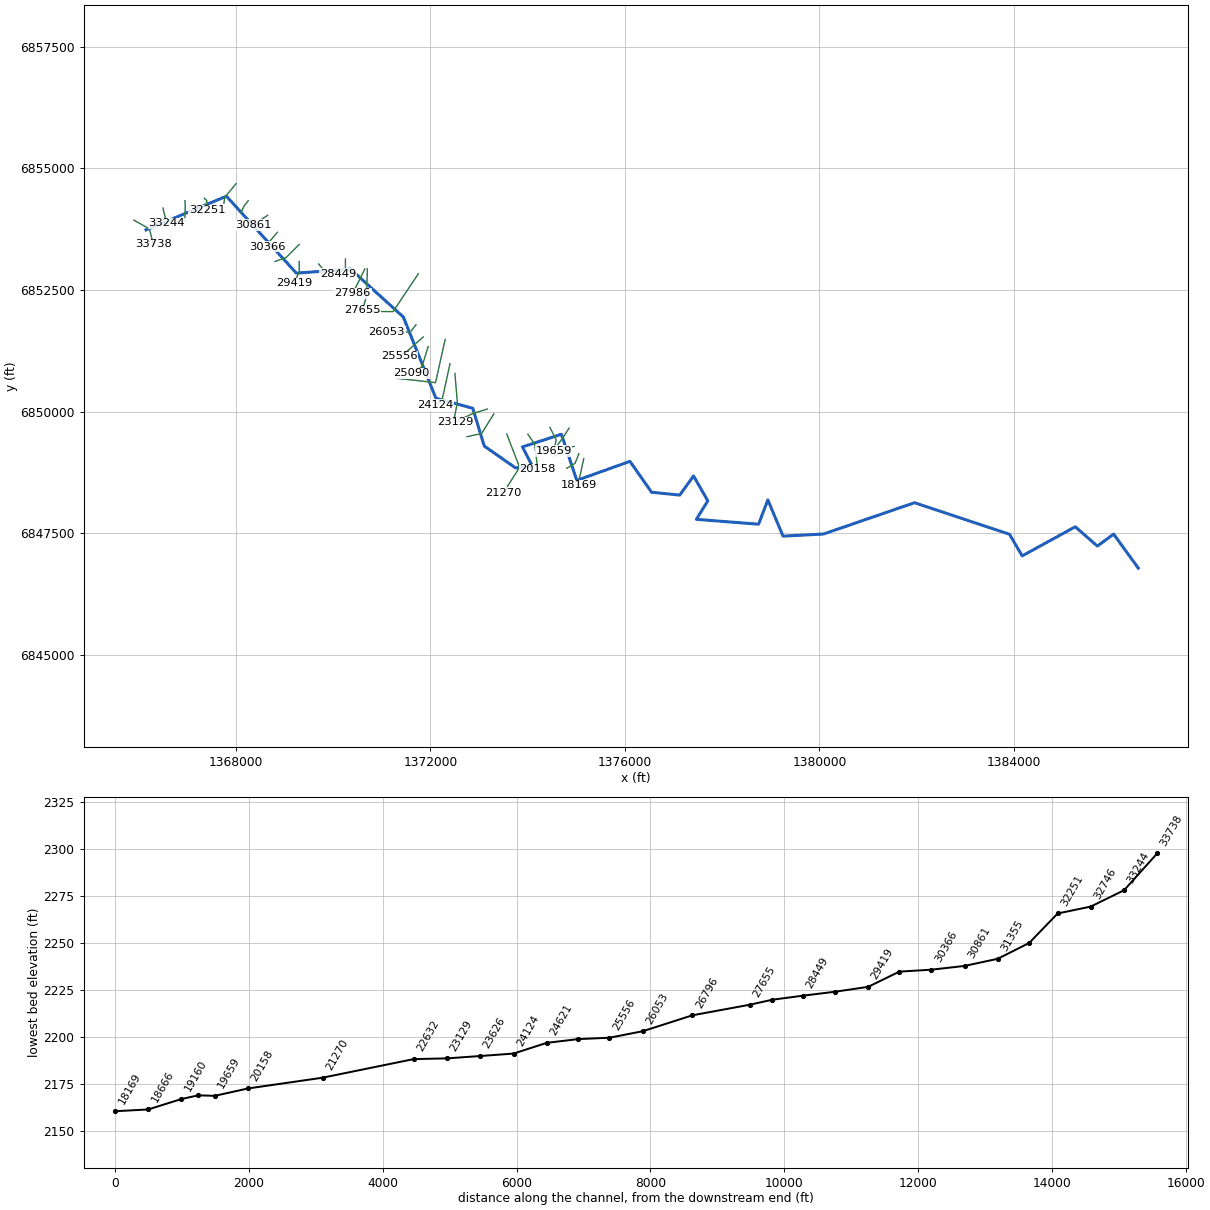
--- Sweetwater Creek Trib 21.prj (project) ---

Proj Title=Sweetwater Creek Trib 21 Base Level Engineering
Current Plan=p01
Default Exp/Contr=0.3,0.1
English Units
Geom File=g01
Flow File=f01
Plan File=p01
BEGIN DESCRIPTION:
Sweetwater Creek Trib 21
END DESCRIPTION:

--- Sweetwater Creek Trib 21.p01 (plan) ---

Plan Title=Multiple Run
Short Identifier=Multiple
Geom File=g01
Flow File=f01
Subcritical Flow
K Sum by GR= 0
Std Step Tol= 0.01
Critical Tol= 0.01
Num of Std Step Trials= 20
Max Error Tol= 0.3
Flow Tol Ratio= 0.001
Split Flow NTrial= 30
Split Flow Tol= 0.02
Split Flow Ratio= 0.02
Log Output Level= 0
Friction Slope Method= 1
Unsteady Friction Slope Method= 2
Unsteady Bridges Friction Slope Method= 1
Parabolic Critical Depth
Global Vel Dist=  1 , 1 , 1
Global Log Level= 0
CheckData=True
Encroach Param= -1, 0, 0, 0
BEGIN DESCRIPTION:
Multiple Run
END DESCRIPTION:

--- Sweetwater Creek Trib 21.f01 (steady flow) ---

Flow Title=Multiple
Number of Profiles=7
Profile Names=10-year,25-year,50-year,1pct_min,100-year,1pct_plu,500-year
River Rch & RM= Sweetwater Creek,Reach-1,33738
     279     402     506     317     633    1263    1004
River Rch & RM= Sweetwater Creek,Reach-1,26796
     367     532     675     425     849    1693    1360
River Rch & RM= Sweetwater Creek,Reach-1,24124
     459     672     856     542    1082    2159    1752
River Rch & RM= Sweetwater Creek,Reach-1,20158
     540     792    1010     639    1275    2545    2061
River Rch & RM= Sweetwater Creek,Reach-1,10786
     547     802    1022     647    1290    2574    2084
River Rch & RM= Sweetwater Creek,Reach-1,8673
     678    1005    1291     822    1640    3273    2687
River Rch & RM= Sweetwater Creek,Reach-1,6859
     715    1057    1354     860    1715    3422    2792
Boundary for River Rch & Prof#=Sweetwater Creek,Reach-1,1
Up Type=0
Dn Type=3
Dn Slope=0.005
Boundary for River Rch & Prof#=Sweetwater Creek,Reach-1,2
Up Type=0
Dn Type=3
Dn Slope=0.005
Boundary for River Rch & Prof#=Sweetwater Creek,Reach-1,3
Up Type=0
Dn Type=3
Dn Slope=0.005
Boundary for River Rch & Prof#=Sweetwater Creek,Reach-1,4
Up Type=0
Dn Type=3
Dn Slope=0.005
Boundary for River Rch & Prof#=Sweetwater Creek,Reach-1,5
Up Type=0
Dn Type=3
Dn Slope=0.005
Boundary for River Rch & Prof#=Sweetwater Creek,Reach-1,6
Up Type=0
Dn Type=3
Dn Slope=0.005
Boundary for River Rch & Prof#=Sweetwater Creek,Reach-1,7
Up Type=0
Dn Type=3
Dn Slope=0.005

--- Sweetwater Creek Trib 21.g01 (geometry) ---

Geom Title=Existing Conditions

River Reach=Sweetwater Creek,Reach-1
Reach XY= 30
      1366155.00      6853738.00      1367808.23      6854430.15
      1369244.62      6852848.97      1370361.19      6852930.19
      1371444.07      6851948.43      1372115.30      6850277.68
      1372872.64      6850071.56      1373108.66      6849296.17
      1373751.65      6848845.99      1374097.35      6848884.31
      1373894.82      6849277.68      1374695.17      6849537.32
      1375010.39      6848589.65      1376104.65      6848980.79
      1376548.83      6848345.86      1377127.88      6848287.63
      1377411.34      6848679.98      1377705.45      6848169.65
      1377469.68      6847788.88      1378748.77      6847689.33
      1378939.53      6848188.01      1379252.26      6847443.33
      1380084.95      6847487.79      1381954.99      6848130.47
      1383907.74      6847482.66      1384168.90      6847038.29
      1385260.36      6847636.04      1385714.71      6847239.24
      1386049.48      6847485.65      1386555.00      6846788.00

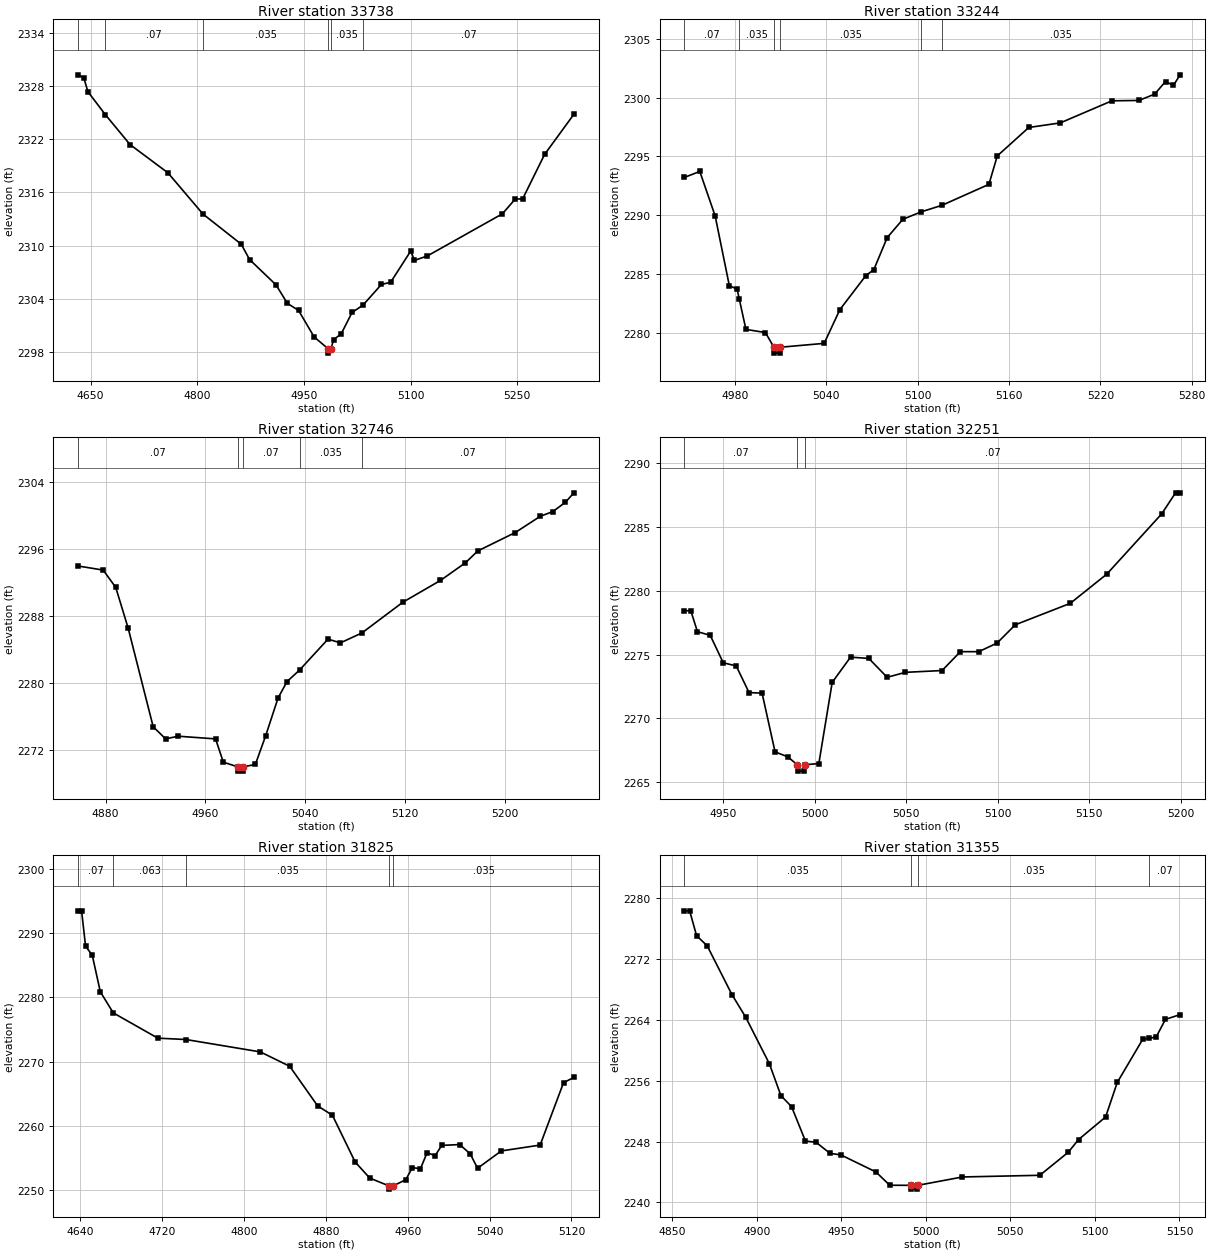
Type RM Length L Ch R = 1,33738,494,494,494
BEGIN DESCRIPTION:
Sweetwater Creek Trib 21 60.0
END DESCRIPTION:
XS GIS Cut Line= 3
      1365905.04      6853937.98      1366225.09      6853757.78
      1366305.00      6853438.01
#Sta/Elev= 30
  4632.7 2329.31  4640.6 2328.96  4646.4 2327.40  4670.7 2324.82  4705.6 2321.42
  4758.9 2318.22  4808.0 2313.57  4861.8 2310.16  4873.7 2308.41  4910.8 2305.55
  4926.8 2303.46  4942.5 2302.66  4964.4 2299.66  4984.0 2298.33  4984.3 2297.83
  4988.0 2298.33  4991.8 2299.35  5002.5 2300.02  5017.7 2302.43  5033.1 2303.26
  5059.0 2305.60  5071.9 2305.84  5100.2 2309.38  5105.4 2308.32  5123.5 2308.82
  5229.1 2313.59  5247.2 2315.27  5257.5 2315.27  5288.4 2320.31  5329.6 2324.85
#Mann=6,-1,0
  4632.7   0.035       0  4670.7    0.07       0  4808.0   0.035       0
  4984.0   0.035       0  4988.0   0.035       0  5033.1    0.07       0
Bank Sta=4984,4988
Exp/Cntr=0.3,0.1

Type RM Length L Ch R = 1,33244,498,498,498
BEGIN DESCRIPTION:
Sweetwater Creek Trib 21 59.0
END DESCRIPTION:
XS GIS Cut Line= 3
      1366505.01      6854187.96      1366512.86      6854135.34
      1366581.95      6853871.85
#Sta/Elev= 30
  4946.8 2293.20  4956.9 2293.71  4967.0 2289.92  4976.3 2283.99  4981.4 2283.70
  4982.8 2282.87  4987.2 2280.27  5000.0 2280.00  5005.6 2278.75  5005.8 2278.25
  5009.3 2278.25  5009.6 2278.75  5038.6 2279.08  5048.9 2281.95  5066.0 2284.85
  5071.2 2285.35  5080.0 2288.08  5090.3 2289.64  5102.3 2290.27  5116.0 2290.83
  5146.8 2292.61  5152.3 2295.03  5173.0 2297.45  5193.7 2297.84  5227.6 2299.72
  5245.4 2299.75  5255.7 2300.29  5262.8 2301.36  5268.0 2301.03  5272.4 2301.93
#Mann=6,-1,0
  4946.8    0.07       0  4982.8   0.035       0  5005.6   0.035       0
  5009.6   0.035       0  5102.3    0.07       0  5116.0   0.035       0
Bank Sta=5005.6,5009.6
Exp/Cntr=0.3,0.1

Type RM Length L Ch R = 1,32746,495,495,495
BEGIN DESCRIPTION:
Sweetwater Creek Trib 21 58.0
END DESCRIPTION:
XS GIS Cut Line= 3
      1366955.00      6854338.03      1366961.05      6854196.16
      1366951.37      6853941.04
#Sta/Elev= 30
  4858.0 2293.97  4878.0 2293.49  4888.1 2291.42  4898.1 2286.54  4918.1 2274.82
  4928.1 2273.38  4938.1 2273.70  4968.1 2273.38  4974.3 2270.61  4986.1 2270.04
  4986.4 2269.54  4989.9 2269.54  4990.1 2270.04  5000.0 2270.34  5008.2 2273.73
  5018.2 2278.26  5025.4 2280.21  5035.4 2281.58  5058.2 2285.26  5068.2 2284.82
  5085.4 2286.00  5118.2 2289.66  5148.3 2292.25  5168.3 2294.35  5178.3 2295.77
  5208.3 2297.96  5228.3 2299.89  5238.3 2300.45  5248.3 2301.54  5255.3 2302.69
#Mann=5,-1,0
  4858.0    0.07       0  4986.1    0.07       0  4990.1    0.07       0
  5035.4   0.035       0  5085.4    0.07       0
Bank Sta=4986.1,4990.1
Exp/Cntr=0.3,0.1

Type RM Length L Ch R = 1,32251,426,426,426
BEGIN DESCRIPTION:
Sweetwater Creek Trib 21 57.0
END DESCRIPTION:
XS GIS Cut Line= 3
      1367355.01      6854387.99      1367405.17      6854337.60
      1367405.00      6854138.00
#Sta/Elev= 30
  4928.9 2278.44  4932.4 2278.44  4936.0 2276.80  4943.0 2276.51  4950.1 2274.36
  4957.2 2274.11  4964.2 2272.02  4971.3 2271.98  4978.4 2267.37  4985.4 2266.98
  4990.5 2266.36  4990.8 2265.86  4994.3 2265.86  4994.5 2266.36  5002.3 2266.45
  5009.6 2272.82  5019.6 2274.80  5029.6 2274.70  5039.6 2273.22  5049.6 2273.61
  5069.6 2273.75  5079.6 2275.23  5089.6 2275.23  5099.6 2275.90  5109.6 2277.34
  5139.6 2279.02  5159.6 2281.32  5189.6 2286.05  5197.1 2287.69  5199.6 2287.69
#Mann=3,-1,0
  4928.9    0.07       0  4990.5    0.07       0  4994.5    0.07       0
Bank Sta=4990.5,4994.5
Exp/Cntr=0.3,0.1

Type RM Length L Ch R = 1,31825,470,470,470
BEGIN DESCRIPTION:
Sweetwater Creek Trib 21 56.0
END DESCRIPTION:
XS GIS Cut Line= 3
      1368005.03      6854688.03      1367774.98      6854408.78
      1367755.00      6854288.03
#Sta/Elev= 30
  4638.2 2293.48  4641.5 2293.48  4645.4 2287.96  4651.9 2286.59  4659.8 2280.87
  4672.5 2277.58  4716.0 2273.65  4743.4 2273.44  4816.1 2271.51  4844.8 2269.27
  4872.1 2263.10  4886.5 2261.65  4908.7 2254.37  4923.0 2251.86  4941.8 2250.64
  4942.1 2250.14  4945.8 2250.64  4958.2 2251.61  4964.6 2253.50  4972.5 2253.31
  4979.0 2255.82  4986.8 2255.35  4993.3 2256.95  5010.9 2257.08  5021.1 2255.63
  5028.3 2253.39  5051.5 2256.09  5089.4 2257.00  5112.3 2266.73  5122.4 2267.53
#Mann=5,-1,0
  4638.2    0.07       0  4672.5   0.063       0  4743.4   0.035       0
  4941.8   0.035       0  4945.8   0.035       0
Bank Sta=4941.8,4945.8
Exp/Cntr=0.3,0.1

Type RM Length L Ch R = 1,31355,494,494,494
BEGIN DESCRIPTION:
Sweetwater Creek Trib 21 55.0
END DESCRIPTION:
XS GIS Cut Line= 3
      1368254.99      6854337.98      1368168.24      6854224.43
      1368104.99      6854087.97
#Sta/Elev= 30
  4857.1 2278.35  4860.2 2278.35  4864.3 2275.08  4870.6 2273.74  4885.2 2267.34
  4893.4 2264.34  4907.4 2258.22  4914.2 2254.04  4920.5 2252.59  4928.7 2248.07
  4935.0 2247.90  4943.3 2246.44  4949.6 2246.25  4970.4 2244.00  4978.6 2242.25
  4991.2 2242.24  4991.4 2241.74  4994.9 2241.74  4995.2 2242.24  5021.6 2243.34
  5067.4 2243.56  5084.2 2246.59  5090.3 2248.26  5106.3 2251.23  5113.2 2255.77
  5128.3 2261.46  5132.1 2261.59  5136.2 2261.74  5141.7 2264.07  5150.4 2264.70
#Mann=4,-1,0
  4857.1   0.035       0  4991.2   0.035       0  4995.2   0.035       0
  5132.1    0.07       0
Bank Sta=4991.2,4995.2
Exp/Cntr=0.3,0.1

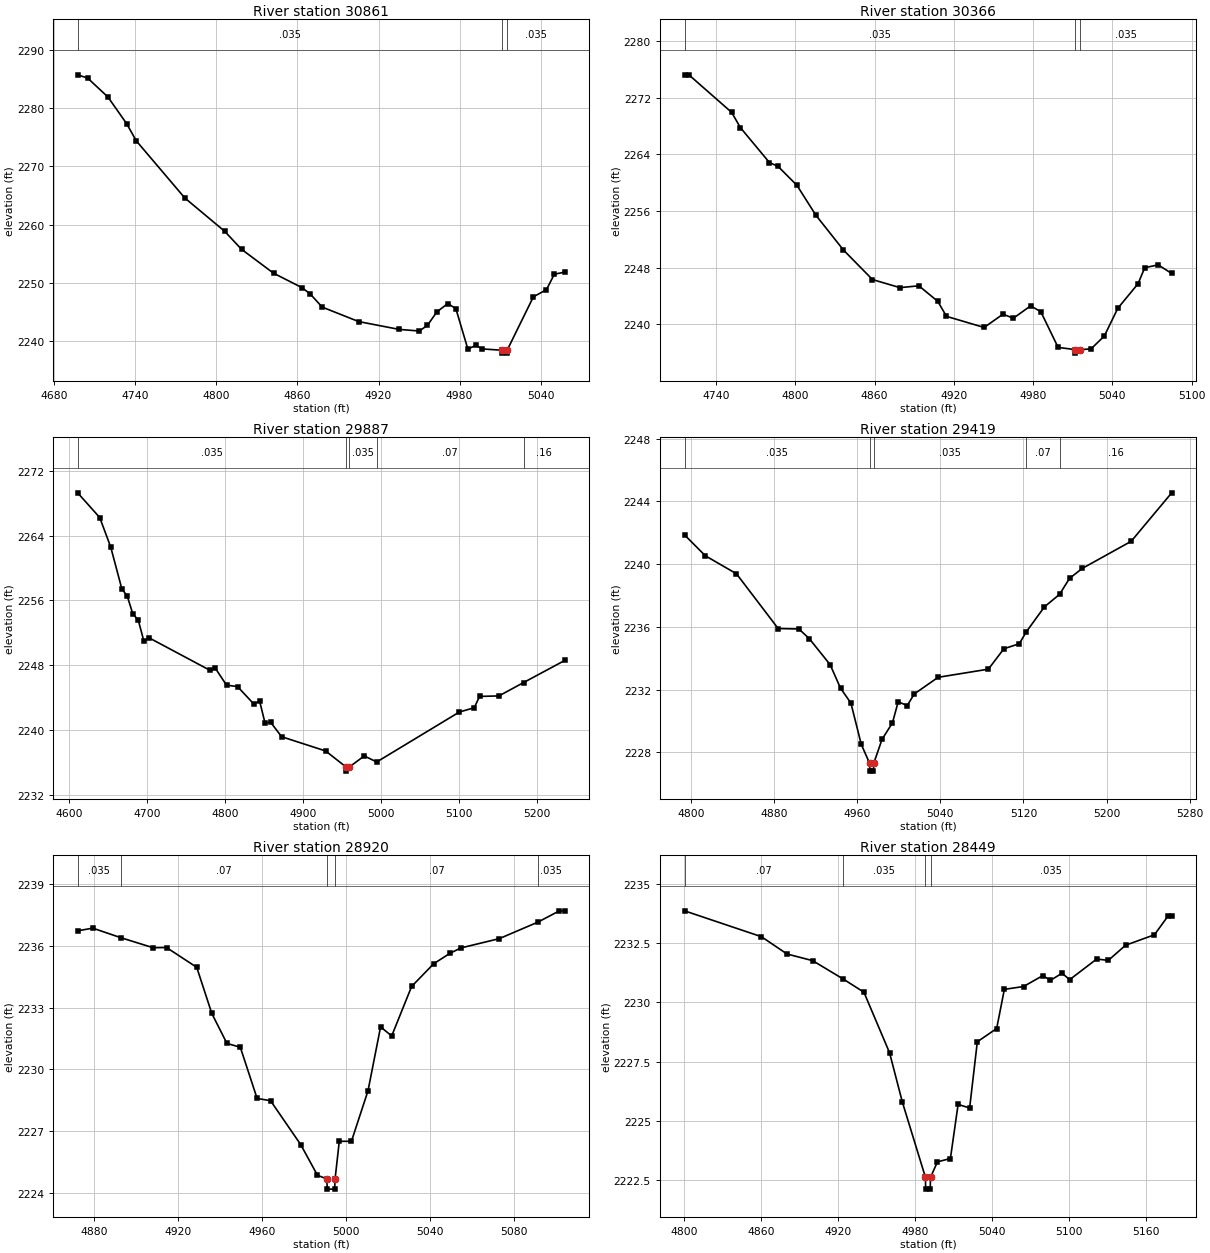
Type RM Length L Ch R = 1,30861,495,495,495
BEGIN DESCRIPTION:
Sweetwater Creek Trib 21 54.0
END DESCRIPTION:
XS GIS Cut Line= 3
      1368654.96      6854037.98      1368404.60      6853867.84
      1368354.99      6853837.99
#Sta/Elev= 30
  4697.3 2285.66  4704.7 2285.10  4719.7 2281.86  4733.5 2277.31  4740.7 2274.34
  4776.6 2264.55  4806.1 2258.84  4818.6 2255.75  4842.3 2251.65  4863.4 2249.17
  4869.4 2248.10  4878.3 2245.84  4905.3 2243.36  4935.2 2242.02  4950.2 2241.74
  4956.2 2242.72  4963.2 2245.02  4971.2 2246.44  4977.2 2245.60  4986.1 2238.65
  4992.1 2239.29  4996.7 2238.67  5011.2 2238.45  5011.5 2237.95  5015.0 2237.95
  5015.2 2238.45  5034.6 2247.60  5044.3 2248.83  5050.1 2251.48  5057.9 2251.84
#Mann=3,-1,0
  4697.3   0.035       0  5011.2   0.035       0  5015.2   0.035       0
Bank Sta=5011.2,5015.2
Exp/Cntr=0.3,0.1

Type RM Length L Ch R = 1,30366,479,479,479
BEGIN DESCRIPTION:
Sweetwater Creek Trib 21 53.0
END DESCRIPTION:
XS GIS Cut Line= 3
      1368854.99      6853687.99      1368671.58      6853471.30
      1368655.01      6853388.03
#Sta/Elev= 30
  4716.1 2275.22  4719.4 2275.22  4751.8 2269.92  4758.4 2267.77  4780.4 2262.84
  4786.9 2262.30  4801.2 2259.63  4815.5 2255.42  4836.4 2250.50  4858.4 2246.33
  4879.2 2245.19  4893.5 2245.45  4907.8 2243.26  4914.4 2241.14  4942.9 2239.57
  4957.2 2241.45  4965.0 2240.87  4978.1 2242.62  4985.8 2241.80  4998.9 2236.76
  5011.6 2236.45  5011.8 2235.95  5015.6 2236.45  5023.8 2236.54  5033.9 2238.37
  5044.1 2242.28  5059.4 2245.74  5064.5 2248.01  5074.7 2248.40  5084.9 2247.19
#Mann=3,-1,0
  4716.1   0.035       0  5011.6   0.035       0  5015.6   0.035       0
Bank Sta=5011.6,5015.6
Exp/Cntr=0.3,0.1

Type RM Length L Ch R = 1,29887,468,468,468
BEGIN DESCRIPTION:
Sweetwater Creek Trib 21 52.0
END DESCRIPTION:
XS GIS Cut Line= 3
      1369305.02      6853438.02      1369028.38      6853164.69
      1368804.98      6853087.99
#Sta/Elev= 30
  4611.1 2269.30  4639.4 2266.25  4653.5 2262.61  4667.7 2257.47  4674.8 2256.52
  4681.8 2254.37  4688.9 2253.56  4695.9 2251.03  4703.1 2251.37  4780.8 2247.38
  4787.9 2247.61  4802.1 2245.54  4816.2 2245.37  4837.4 2243.18  4844.5 2243.60
  4851.5 2240.86  4858.6 2240.97  4872.8 2239.17  4929.3 2237.41  4955.6 2235.42
  4955.9 2234.92  4959.6 2235.42  4978.8 2236.80  4994.8 2236.05  5100.8 2242.22
  5119.9 2242.75  5126.8 2244.15  5151.6 2244.21  5183.2 2245.86  5236.2 2248.60
#Mann=5,-1,0
  4611.1   0.035       0  4955.6    0.07       0  4959.6   0.035       0
  4994.8    0.07       0  5183.2    0.16       0
Bank Sta=4955.6,4959.6
Exp/Cntr=0.3,0.1

Type RM Length L Ch R = 1,29419,499,499,499
BEGIN DESCRIPTION:
Sweetwater Creek Trib 21 51.0
END DESCRIPTION:
XS GIS Cut Line= 3
      1369305.00      6853088.05      1369302.53      6852881.96
      1369205.01      6852638.03
#Sta/Elev= 30
  4793.9 2241.86  4813.9 2240.53  4843.9 2239.38  4884.0 2235.89  4904.0 2235.86
  4914.0 2235.24  4934.0 2233.59  4944.0 2232.09  4954.0 2231.14  4964.0 2228.50
  4972.0 2227.30  4972.2 2226.80  4975.7 2226.80  4976.0 2227.30  4984.0 2228.83
  4994.0 2229.88  4999.5 2231.22  5008.2 2230.98  5015.0 2231.72  5037.9 2232.78
  5086.3 2233.30  5101.2 2234.60  5116.0 2234.92  5122.8 2235.68  5140.2 2237.27
  5154.8 2238.07  5164.4 2239.09  5176.6 2239.72  5223.7 2241.45  5262.7 2244.54
#Mann=5,-1,0
  4793.9   0.035       0  4972.0   0.035       0  4976.0   0.035       0
  5122.8    0.07       0  5154.8    0.16       0
Bank Sta=4972,4976
Exp/Cntr=0.3,0.1

Type RM Length L Ch R = 1,28920,471,471,471
BEGIN DESCRIPTION:
Sweetwater Creek Trib 21 50.0
END DESCRIPTION:
XS GIS Cut Line= 3
      1369705.03      6853037.97      1369784.99      6852938.02
      1369755.01      6852838.02
#Sta/Elev= 30
  4872.0 2236.72  4879.2 2236.85  4892.5 2236.39  4908.0 2235.90  4914.4 2235.91
  4928.8 2234.95  4936.0 2232.71  4943.2 2231.26  4949.6 2231.07  4957.6 2228.59
  4964.0 2228.48  4978.4 2226.35  4986.4 2224.86  4990.8 2224.69  4991.1 2224.19
  4994.6 2224.19  4994.8 2224.69  4996.8 2226.51  5002.6 2226.51  5010.5 2228.96
  5016.5 2232.06  5021.8 2231.62  5031.3 2234.02  5041.8 2235.12  5049.6 2235.63
  5054.8 2235.89  5073.1 2236.34  5091.5 2237.14  5101.8 2237.69  5104.4 2237.69
#Mann=5,-1,0
  4872.0   0.035       0  4892.5    0.07       0  4990.8    0.07       0
  4994.8    0.07       0  5091.5   0.035       0
Bank Sta=4990.8,4994.8
Exp/Cntr=0.3,0.1

Type RM Length L Ch R = 1,28449,463,463,463
BEGIN DESCRIPTION:
Sweetwater Creek Trib 21 49.0
END DESCRIPTION:
XS GIS Cut Line= 3
      1370255.00      6853137.98      1370255.03      6852938.08
      1370105.04      6852838.03
#Sta/Elev= 30
  4800.1 2233.86  4860.1 2232.77  4880.1 2232.04  4900.1 2231.76  4924.1 2230.98
  4940.1 2230.43  4960.1 2227.88  4970.1 2225.80  4988.1 2222.63  4988.3 2222.13
  4991.8 2222.13  4992.1 2222.63  4997.5 2223.28  5007.6 2223.42  5013.6 2225.70
  5022.6 2225.55  5028.6 2228.34  5043.7 2228.90  5049.7 2230.55  5064.7 2230.67
  5079.7 2231.13  5085.7 2230.93  5094.7 2231.23  5100.7 2230.96  5121.8 2231.83
  5130.8 2231.77  5144.3 2232.41  5166.8 2232.85  5177.3 2233.63  5180.3 2233.63
#Mann=4,-1,0
  4800.1    0.07       0  4924.1   0.035       0  4988.1   0.035       0
  4992.1   0.035       0
Bank Sta=4988.1,4992.1
Exp/Cntr=0.3,0.1

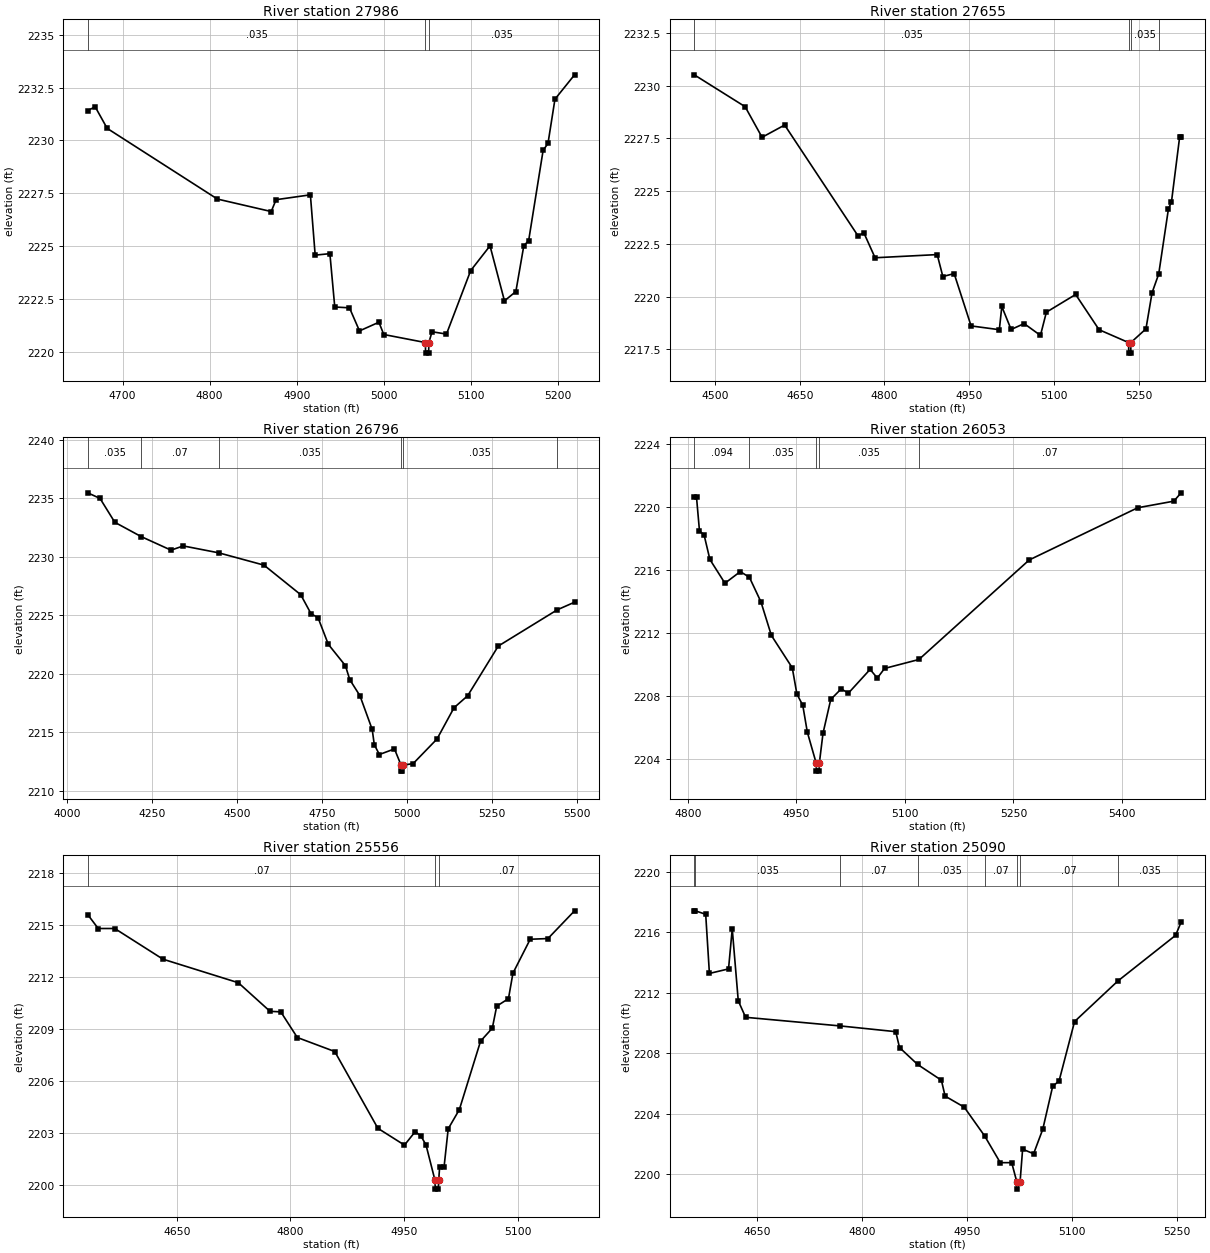
Type RM Length L Ch R = 1,27986,331,331,331
BEGIN DESCRIPTION:
Sweetwater Creek Trib 21 48.0
END DESCRIPTION:
XS GIS Cut Line= 3
      1370655.02      6852938.03      1370504.91      6852632.96
      1370404.99      6852437.97
#Sta/Elev= 30
  4660.0 2231.41  4668.5 2231.59  4682.3 2230.57  4808.9 2227.23  4870.7 2226.64
  4876.3 2227.20  4915.7 2227.43  4921.2 2224.58  4938.1 2224.65  4943.7 2222.13
  4960.6 2222.09  4972.1 2221.00  4994.4 2221.41  5000.0 2220.83  5047.8 2220.45
  5048.0 2219.95  5051.5 2219.95  5051.8 2220.45  5055.4 2220.96  5072.0 2220.85
  5099.8 2223.85  5122.0 2225.02  5138.6 2222.42  5151.7 2222.86  5160.8 2225.02
  5166.4 2225.27  5183.0 2229.53  5188.6 2229.86  5196.6 2231.95  5219.1 2233.10
#Mann=3,-1,0
  4660.0   0.035       0  5047.8   0.035       0  5051.8   0.035       0
Bank Sta=5047.8,5051.8
Exp/Cntr=0.3,0.1

Type RM Length L Ch R = 1,27655,859,859,859
BEGIN DESCRIPTION:
Sweetwater Creek Trib 21 47.0
END DESCRIPTION:
XS GIS Cut Line= 3
      1370705.00      6852937.98      1370691.81      6852401.44
      1370605.01      6852088.04
#Sta/Elev= 30
  4463.3 2230.51  4553.3 2229.00  4583.3 2227.55  4623.3 2228.13  4753.4 2222.87
  4763.4 2223.03  4783.4 2221.84  4893.4 2221.99  4903.4 2220.95  4923.4 2221.09
  4953.4 2218.61  5003.4 2218.43  5007.8 2219.53  5024.3 2218.44  5047.3 2218.72
  5076.2 2218.16  5086.7 2219.26  5138.5 2220.10  5180.0 2218.43  5232.3 2217.82
  5232.6 2217.32  5236.1 2217.32  5236.3 2217.82  5263.0 2218.47  5273.8 2220.18
  5285.6 2221.07  5302.9 2224.17  5308.1 2224.47  5322.6 2227.55  5325.2 2227.55
#Mann=4,-1,0
  4463.3   0.035       0  5232.3   0.035       0  5236.3   0.035       0
  5285.6   0.094       0
Bank Sta=5232.3,5236.3
Exp/Cntr=0.3,0.1

Type RM Length L Ch R = 1,26796,743,743,743
BEGIN DESCRIPTION:
Sweetwater Creek Trib 21 46.0
END DESCRIPTION:
XS GIS Cut Line= 3
      1371755.02      6852838.03      1371234.03      6852057.90
      1370740.67      6852063.97
#Sta/Elev= 30
  4061.9 2235.47  4098.0 2234.99  4141.5 2232.95  4218.9 2231.73  4306.7 2230.57
  4342.8 2230.93  4447.1 2230.34  4580.1 2229.29  4688.2 2226.76  4718.2 2225.15
  4739.3 2224.78  4769.3 2222.52  4819.5 2220.70  4832.4 2219.50  4862.4 2218.12
  4898.4 2215.24  4904.5 2213.94  4919.5 2213.10  4963.8 2213.58  4983.4 2212.18
  4983.7 2211.68  4987.3 2211.68  4987.6 2212.18  5019.0 2212.33  5089.0 2214.43
  5139.0 2217.10  5179.0 2218.12  5269.1 2222.37  5442.6 2225.47  5493.4 2226.12
#Mann=6,-1,0
  4061.9   0.035       0  4218.9    0.07       0  4447.1   0.035       0
  4983.4   0.035       0  4987.6   0.035       0  5442.6   0.094       0
Bank Sta=4983.4,4987.6
Exp/Cntr=0.3,0.1

Type RM Length L Ch R = 1,26053,497,497,497
BEGIN DESCRIPTION:
Sweetwater Creek Trib 21 45.0
END DESCRIPTION:
XS GIS Cut Line= 3
      1371704.97      6851787.97      1371586.76      6851637.57
      1371104.96      6851638.00
#Sta/Elev= 30
  4808.7 2220.61  4811.8 2220.61  4815.9 2218.47  4822.2 2218.23  4830.3 2216.66
  4851.1 2215.15  4872.3 2215.89  4884.9 2215.53  4900.9 2213.96  4915.3 2211.83
  4944.2 2209.77  4950.6 2208.10  4958.7 2207.39  4965.0 2205.68  4977.3 2203.70
  4977.6 2203.20  4981.3 2203.20  4981.6 2203.70  4986.7 2205.61  4997.4 2207.76
  5011.8 2208.43  5021.8 2208.16  5051.8 2209.67  5061.8 2209.12  5071.8 2209.73
  5119.3 2210.30  5271.8 2216.63  5421.8 2219.95  5471.8 2220.37  5481.8 2220.90
#Mann=5,-1,0
  4808.7   0.094       0  4884.9   0.035       0  4977.3   0.035       0
  4981.6   0.035       0  5119.3    0.07       0
Bank Sta=4977.3,4981.6
Exp/Cntr=0.3,0.1

Type RM Length L Ch R = 1,25556,466,466,466
BEGIN DESCRIPTION:
Sweetwater Creek Trib 21 44.0
END DESCRIPTION:
XS GIS Cut Line= 3
      1371855.02      6851538.01      1371504.45      6851228.72
      1371355.03      6851138.02
#Sta/Elev= 30
  4532.5 2215.58  4546.3 2214.78  4568.1 2214.78  4631.7 2213.01  4731.2 2211.65
  4773.0 2210.00  4787.2 2209.97  4809.0 2208.49  4858.4 2207.68  4915.3 2203.25
  4950.4 2202.28  4964.6 2203.06  4972.2 2202.80  4978.8 2202.29  4990.7 2200.24
  4991.0 2199.74  4995.1 2199.74  4995.5 2200.24  4996.8 2201.01  5002.6 2201.01
  5008.1 2203.22  5022.8 2204.33  5050.8 2208.28  5066.3 2209.03  5072.1 2210.30
  5087.6 2210.73  5093.5 2212.20  5116.3 2214.16  5139.7 2214.20  5174.8 2215.80
#Mann=3,-1,0
  4532.5    0.07       0  4990.7    0.07       0  4995.5    0.07       0
Bank Sta=4990.7,4995.5
Exp/Cntr=0.3,0.1

Type RM Length L Ch R = 1,25090,469,469,469
BEGIN DESCRIPTION:
Sweetwater Creek Trib 21 43.0
END DESCRIPTION:
XS GIS Cut Line= 3
      1371955.01      6851338.02      1371825.03      6850918.07
      1371605.00      6850788.00
#Sta/Elev= 30
  4560.4 2217.41  4562.0 2217.41  4576.7 2217.18  4582.0 2213.27  4609.3 2213.57
  4614.6 2216.22  4623.2 2211.46  4633.7 2210.37  4768.8 2209.80  4848.1 2209.42
  4853.5 2208.37  4879.4 2207.25  4913.3 2206.21  4918.6 2205.16  4945.9 2204.43
  4975.0 2202.53  4997.4 2200.76  5013.7 2200.76  5020.9 2199.51  5021.2 2199.01
  5025.7 2199.51  5029.3 2201.65  5045.0 2201.35  5058.1 2202.97  5072.2 2205.80
  5081.4 2206.17  5103.5 2210.09  5165.3 2212.77  5247.8 2215.79  5255.6 2216.66
#Mann=8,-1,0
  4560.4    0.07       0  4562.0   0.035       0  4768.8    0.07       0
  4879.4   0.035       0  4975.0    0.07       0  5020.9    0.07       0
  5025.7    0.07       0  5165.3   0.035       0
Bank Sta=5020.9,5025.7
Exp/Cntr=0.3,0.1

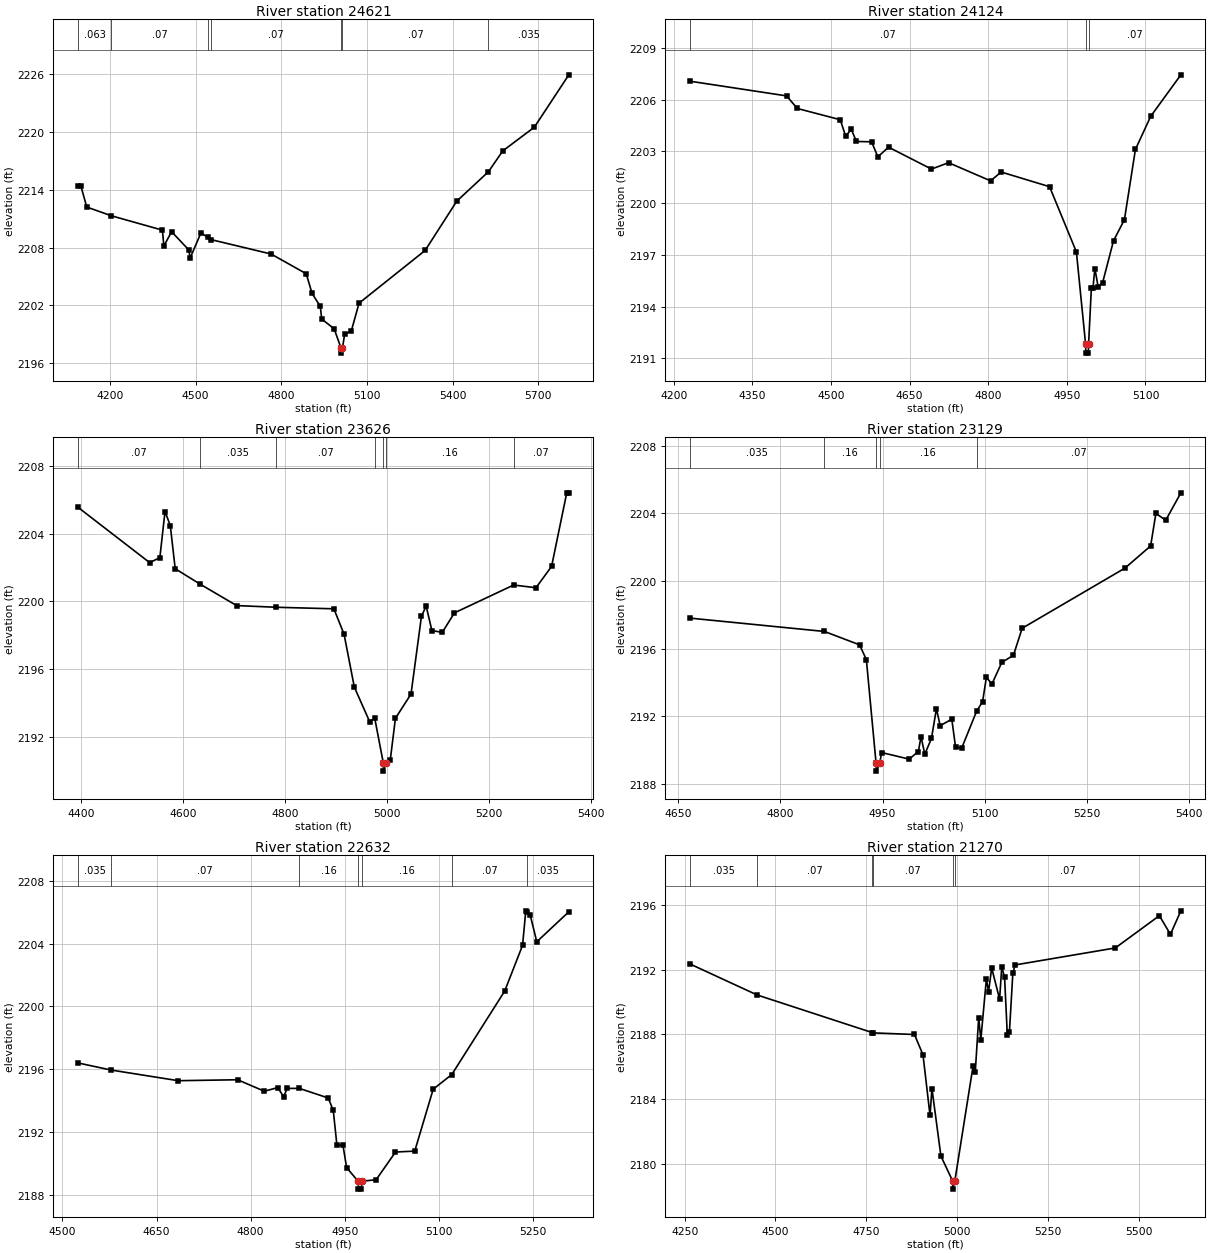
Type RM Length L Ch R = 1,24621,497,497,497
BEGIN DESCRIPTION:
Sweetwater Creek Trib 21 42.0
END DESCRIPTION:
XS GIS Cut Line= 3
      1372305.01      6851488.02      1372106.92      6850598.20
      1371305.03      6850688.00
#Sta/Elev= 30
  4088.4 2214.36  4098.7 2214.39  4119.2 2212.21  4205.7 2211.30  4384.0 2209.81
  4389.1 2208.16  4416.3 2209.65  4476.1 2207.76  4481.2 2206.91  4518.7 2209.51
  4542.7 2209.08  4555.0 2208.82  4764.6 2207.33  4887.5 2205.28  4908.0 2203.23
  4936.7 2201.89  4941.8 2200.57  4985.3 2199.56  5009.6 2197.53  5009.9 2197.03
  5014.4 2197.53  5022.1 2199.02  5045.2 2199.31  5072.4 2202.22  5303.8 2207.70
  5414.5 2212.82  5525.4 2215.88  5575.5 2218.04  5686.2 2220.51  5806.9 2225.95
#Mann=7,-1,0
  4088.4   0.063       0  4205.7    0.07       0  4542.7   0.035       0
  4555.0    0.07       0  5009.6    0.07       0  5014.4    0.07       0
  5525.4   0.035       0
Bank Sta=5009.6,5014.4
Exp/Cntr=0.3,0.1

Type RM Length L Ch R = 1,24124,498,498,498
BEGIN DESCRIPTION:
Sweetwater Creek Trib 21 41.0
END DESCRIPTION:
XS GIS Cut Line= 3
      1372405.01      6850988.03      1372240.26      6850236.99
      1372105.01      6850138.01
#Sta/Elev= 30
  4231.1 2207.06  4415.4 2206.21  4435.9 2205.48  4517.8 2204.83  4528.0 2203.88
  4538.9 2204.27  4548.5 2203.57  4577.6 2203.55  4589.5 2202.68  4609.9 2203.24
  4691.8 2201.97  4724.4 2202.34  4804.5 2201.29  4824.9 2201.80  4917.1 2200.95
  4968.3 2197.17  4985.9 2191.81  4986.4 2191.31  4991.1 2191.31  4991.5 2191.81
  4996.9 2195.11  5000.0 2195.11  5003.5 2196.21  5009.7 2195.16  5018.2 2195.38
  5039.1 2197.82  5059.9 2199.04  5080.9 2203.11  5110.1 2205.03  5167.6 2207.43
#Mann=3,-1,0
  4231.1    0.07       0  4985.9    0.07       0  4991.5    0.07       0
Bank Sta=4985.9,4991.5
Exp/Cntr=0.3,0.1

Type RM Length L Ch R = 1,23626,497,497,497
BEGIN DESCRIPTION:
Sweetwater Creek Trib 21 40.0
END DESCRIPTION:
XS GIS Cut Line= 3
      1372505.00      6850788.05      1372556.50      6850184.54
      1372484.18      6849834.94
#Sta/Elev= 30
  4394.3 2205.55  4534.9 2202.29  4554.9 2202.58  4565.0 2205.30  4575.4 2204.47
  4585.0 2201.93  4634.0 2201.02  4705.5 2199.76  4783.6 2199.66  4896.2 2199.57
  4916.2 2198.07  4936.3 2194.96  4966.4 2192.92  4976.3 2193.13  4993.0 2190.51
  4993.4 2190.01  4998.6 2190.51  5006.7 2190.64  5016.9 2193.12  5047.5 2194.55
  5068.0 2199.14  5077.2 2199.73  5088.4 2198.29  5108.8 2198.18  5132.6 2199.33
  5248.8 2200.97  5292.6 2200.81  5323.2 2202.07  5352.9 2206.40  5357.0 2206.40
#Mann=7,-1,0
  4394.3    0.07       0  4634.0   0.035       0  4783.6    0.07       0
  4976.3    0.16       0  4993.0    0.07       0  4998.6    0.16       0
  5248.8    0.07       0
Bank Sta=4993,4998.6
Exp/Cntr=0.3,0.1

Type RM Length L Ch R = 1,23129,497,497,497
BEGIN DESCRIPTION:
Sweetwater Creek Trib 21 39.0
END DESCRIPTION:
XS GIS Cut Line= 3
      1373172.08      6850056.32      1372854.65      6849956.36
      1372504.97      6849787.99
#Sta/Elev= 30
  4667.2 2197.80  4864.7 2197.01  4916.2 2196.22  4926.2 2195.35  4940.4 2189.25
  4940.9 2188.75  4946.1 2189.25  4948.5 2189.85  4989.1 2189.46  5002.6 2189.91
  5006.5 2190.79  5012.0 2189.75  5021.8 2190.68  5029.1 2192.44  5034.6 2191.44
  5051.7 2191.82  5057.2 2190.17  5066.2 2190.11  5088.2 2192.30  5096.9 2192.86
  5102.5 2194.30  5110.6 2193.90  5125.1 2195.18  5142.2 2195.60  5155.0 2197.20
  5306.1 2200.76  5343.7 2202.07  5351.4 2203.99  5365.9 2203.59  5388.1 2205.21
#Mann=5,-1,0
  4667.2   0.035       0  4864.7    0.16       0  4940.4    0.07       0
  4946.1    0.16       0  5088.2    0.07       0
Bank Sta=4940.4,4946.1
Exp/Cntr=0.3,0.1

Type RM Length L Ch R = 1,22632,1362,1362,1362
BEGIN DESCRIPTION:
Sweetwater Creek Trib 21 38.0
END DESCRIPTION:
XS GIS Cut Line= 3
      1373305.26      6849957.23      1373055.14      6849553.06
      1372755.01      6849488.00
#Sta/Elev= 30
  4524.7 2196.40  4577.3 2195.95  4684.6 2195.27  4779.2 2195.33  4821.7 2194.60
  4843.0 2194.83  4852.5 2194.26  4858.3 2194.78  4877.6 2194.78  4923.6 2194.17
  4931.6 2193.38  4937.5 2191.15  4947.0 2191.18  4952.9 2189.74  4971.3 2188.87
  4971.8 2188.37  4976.6 2188.37  4977.0 2188.87  5000.0 2188.97  5030.8 2190.73
  5061.5 2190.79  5090.9 2194.73  5120.5 2195.66  5204.8 2200.97  5233.3 2203.88
  5238.5 2206.08  5240.6 2206.00  5245.7 2205.79  5256.0 2204.11  5307.1 2206.02
#Mann=7,-1,0
  4524.7   0.035       0  4577.3    0.07       0  4877.6    0.16       0
  4971.3    0.07       0  4977.0    0.16       0  5120.5    0.07       0
  5240.6   0.035       0
Bank Sta=4971.3,4977
Exp/Cntr=0.3,0.1

Type RM Length L Ch R = 1,21270,1112,1112,1112
BEGIN DESCRIPTION:
Sweetwater Creek Trib 21 37.0
END DESCRIPTION:
XS GIS Cut Line= 3
      1373571.00      6849544.94      1373834.84      6848858.50
      1373505.00      6848338.01
#Sta/Elev= 30
  4264.6 2192.35  4449.3 2190.44  4766.2 2188.12  4768.6 2188.10  4882.7 2188.00
  4906.2 2186.74  4925.5 2183.01  4930.8 2184.66  4955.5 2180.50  4987.8 2178.96
  4988.3 2178.46  4993.8 2178.96  5044.2 2186.08  5050.1 2185.69  5059.5 2189.03
  5065.4 2187.69  5080.7 2191.43  5086.6 2190.64  5095.3 2192.10  5117.1 2190.18
  5123.0 2192.16  5130.8 2191.52  5138.3 2187.98  5144.2 2188.18  5153.5 2191.77
  5159.5 2192.29  5435.7 2193.34  5557.0 2195.33  5587.4 2194.18  5616.2 2195.63
#Mann=6,-1,0
  4264.6   0.035       0  4449.3    0.07       0  4766.2    0.16       0
  4768.6    0.07       0  4987.8    0.07       0  4993.8    0.07       0
Bank Sta=4987.8,4993.8
Exp/Cntr=0.3,0.1

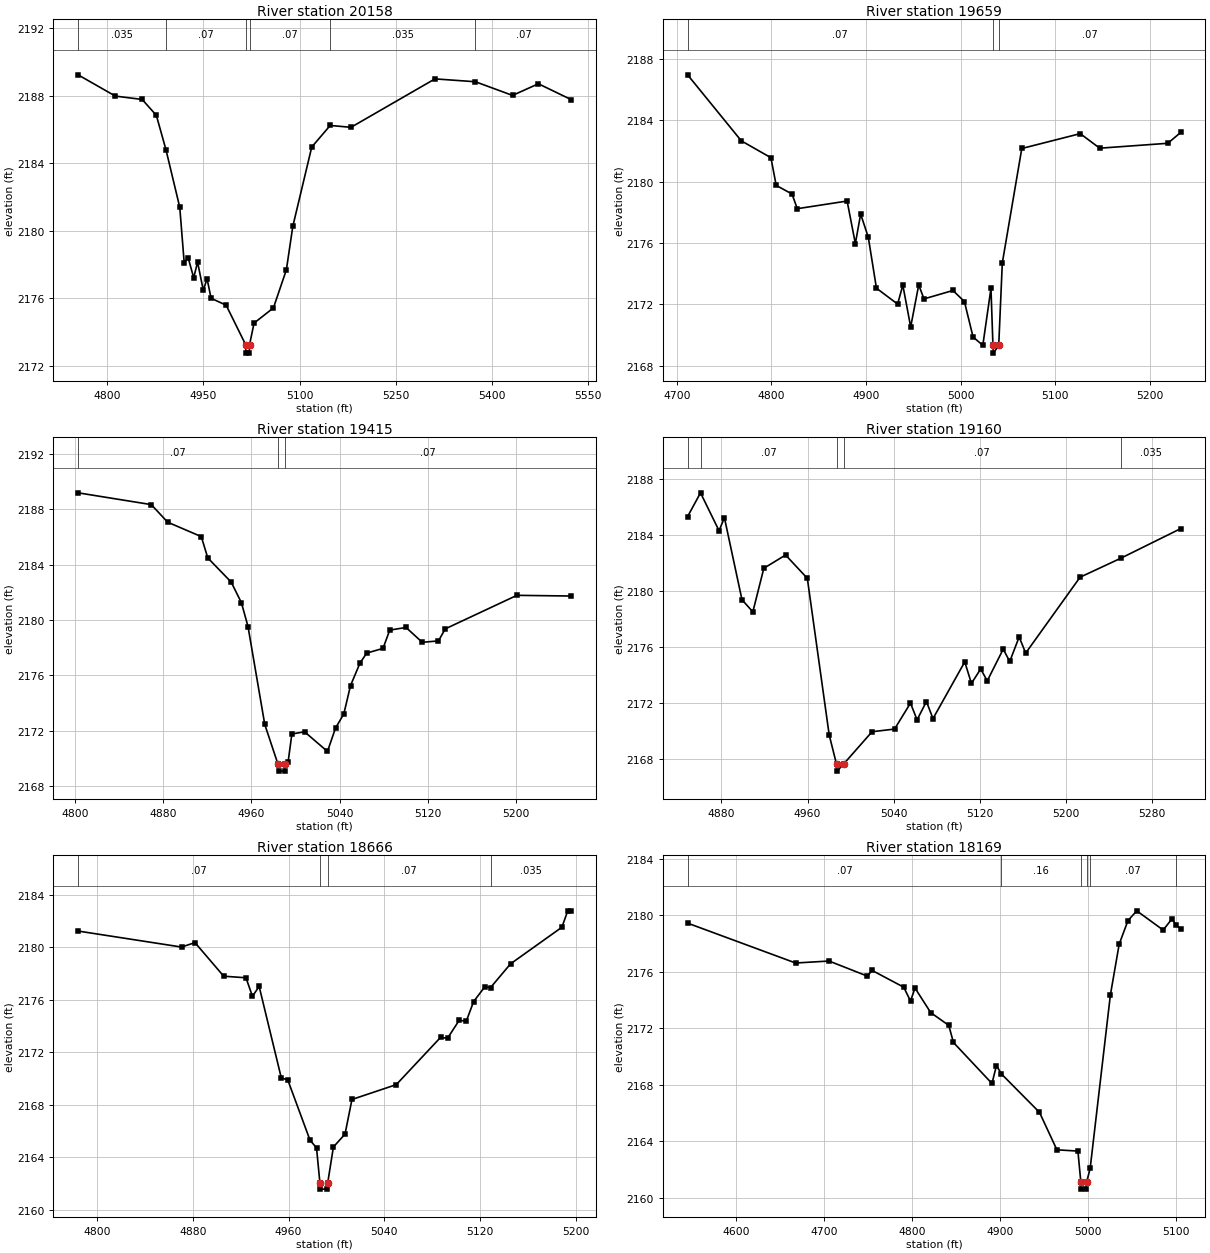
Type RM Length L Ch R = 1,20158,499,499,499
BEGIN DESCRIPTION:
Sweetwater Creek Trib 21 36.0
END DESCRIPTION:
XS GIS Cut Line= 3
      1374004.98      6849538.03      1374145.22      6849336.90
      1374207.94      6848817.17
#Sta/Elev= 30
  4754.8 2189.24  4812.9 2187.98  4854.7 2187.78  4876.8 2186.84  4891.8 2184.80
  4913.3 2181.39  4920.2 2178.11  4926.3 2178.41  4935.0 2177.22  4941.1 2178.14
  4949.9 2176.48  4955.9 2177.15  4962.1 2176.00  4985.6 2175.59  5016.0 2173.25
  5016.5 2172.75  5021.6 2172.75  5022.1 2173.25  5029.1 2174.53  5059.3 2175.43
  5079.5 2177.69  5089.5 2180.26  5119.0 2184.96  5147.8 2186.24  5180.2 2186.13
  5311.1 2189.00  5374.1 2188.83  5432.0 2188.02  5472.3 2188.71  5523.5 2187.77
#Mann=6,-1,0
  4754.8   0.035       0  4891.8    0.07       0  5016.0    0.07       0
  5022.1    0.07       0  5147.8   0.035       0  5374.1    0.07       0
Bank Sta=5016,5022.1
Exp/Cntr=0.3,0.1

Type RM Length L Ch R = 1,19659,244,244,244
BEGIN DESCRIPTION:
Sweetwater Creek Trib 21 35.0
END DESCRIPTION:
XS GIS Cut Line= 3
      1374458.99      6849678.77      1374588.54      6849420.88
      1374532.79      6849194.75
#Sta/Elev= 30
  4711.4 2186.98  4768.2 2182.67  4799.5 2181.57  4805.1 2179.76  4821.8 2179.20
  4827.4 2178.24  4880.1 2178.74  4888.8 2175.96  4894.4 2177.89  4902.5 2176.37
  4911.1 2173.05  4933.5 2172.01  4939.0 2173.25  4947.3 2170.52  4955.8 2173.26
  4961.4 2172.35  4992.0 2172.90  5004.1 2172.18  5013.3 2169.86  5023.6 2169.32
  5032.2 2173.04  5034.3 2169.31  5034.8 2168.81  5040.4 2169.31  5044.2 2174.70
  5064.8 2182.17  5126.6 2183.14  5147.2 2182.19  5219.2 2182.51  5232.9 2183.22
#Mann=3,-1,0
  4711.4    0.07       0  5034.3    0.07       0  5040.4    0.07       0
Bank Sta=5034.3,5040.4
Exp/Cntr=0.3,0.1

Type RM Length L Ch R = 1,19415,255,255,255
BEGIN DESCRIPTION:
Sweetwater Creek Trib 21 4502
END DESCRIPTION:
XS GIS Cut Line= 3
      1374852.07      6849664.03      1374746.29      6849497.48
      1374600.35      6849294.25
#Sta/Elev= 30
  4802.7 2189.18  4869.1 2188.33  4884.0 2187.06  4914.5 2186.02  4920.4 2184.48
  4941.6 2182.74  4950.9 2181.25  4956.9 2179.53  4972.1 2172.46  4984.1 2169.59
  4984.6 2169.09  4990.1 2169.09  4990.6 2169.59  4993.3 2169.76  4996.7 2171.77
  5008.2 2171.93  5029.0 2170.51  5036.3 2172.20  5043.8 2173.21  5049.9 2175.26
  5058.5 2176.89  5064.6 2177.61  5079.4 2177.95  5085.5 2179.27  5100.3 2179.46
  5115.0 2178.39  5129.7 2178.49  5135.9 2179.36  5200.9 2181.78  5250.2 2181.73
#Mann=3,-1,0
  4802.7    0.07       0  4984.1    0.07       0  4990.6    0.07       0
Bank Sta=4984.1,4990.6
Exp/Cntr=0.3,0.1

Type RM Length L Ch R = 1,19160,494,494,494
BEGIN DESCRIPTION:
Sweetwater Creek Trib 21 34.0
END DESCRIPTION:
XS GIS Cut Line= 3
      1374954.95      6849287.99      1374805.29      6849265.16
      1374555.03      6849088.02
#Sta/Elev= 30
  4848.6 2185.32  4860.6 2187.02  4877.8 2184.31  4882.8 2185.24  4899.1 2179.37
  4909.2 2178.50  4919.4 2181.62  4939.6 2182.57  4959.8 2180.90  4980.1 2169.69
  4986.9 2167.60  4987.4 2167.10  4993.4 2167.60  5019.9 2169.92  5040.8 2170.11
  5055.6 2171.97  5061.7 2170.77  5070.4 2172.08  5076.5 2170.86  5106.0 2174.92
  5112.2 2173.38  5120.8 2174.41  5126.9 2173.56  5141.7 2175.83  5147.8 2174.95
  5156.5 2176.70  5162.6 2175.55  5213.1 2180.98  5250.7 2182.33  5306.6 2184.46
#Mann=5,-1,0
  4848.6   0.035       0  4860.6    0.07       0  4986.9    0.07       0
  4993.4    0.07       0  5250.7   0.035       0
Bank Sta=4986.9,4993.4
Exp/Cntr=0.3,0.1

Type RM Length L Ch R = 1,18666,497,497,497
BEGIN DESCRIPTION:
Sweetwater Creek Trib 21 33.0
END DESCRIPTION:
XS GIS Cut Line= 3
      1375055.00      6849137.99      1374973.41      6848938.21
      1374804.97      6848837.98
#Sta/Elev= 30
  4784.2 2181.23  4870.6 2180.01  4881.8 2180.35  4905.8 2177.79  4924.4 2177.67
  4929.8 2176.26  4935.4 2177.01  4953.9 2170.04  4959.3 2169.89  4977.9 2165.29
  4983.3 2164.72  4986.1 2162.07  4986.6 2161.57  4992.2 2161.57  4992.7 2162.07
  4997.4 2164.78  5007.1 2165.76  5012.9 2168.40  5049.9 2169.53  5086.9 2173.13
  5092.7 2173.06  5102.5 2174.44  5108.3 2174.35  5114.5 2175.86  5123.9 2176.99
  5128.6 2176.92  5145.3 2178.73  5188.2 2181.52  5193.1 2182.77  5196.0 2182.77
#Mann=4,-1,0
  4784.2    0.07       0  4986.1    0.07       0  4992.7    0.07       0
  5128.6   0.035       0
Bank Sta=4986.1,4992.7
Exp/Cntr=0.3,0.1

Type RM Length L Ch R = 1,18169,500,500,500
BEGIN DESCRIPTION:
Sweetwater Creek Trib 21 32.0
END DESCRIPTION:
XS GIS Cut Line= 3
      1375154.99      6849037.97      1375057.16      6848593.30
      1375055.00      6848488.03
#Sta/Elev= 30
  4544.7 2179.43  4667.5 2176.61  4705.5 2176.75  4749.2 2175.68  4754.3 2176.09
  4790.4 2174.90  4798.1 2173.92  4803.2 2174.84  4821.1 2173.10  4841.6 2172.20
  4846.9 2170.99  4890.7 2168.09  4895.8 2169.36  4901.5 2168.76  4944.7 2166.05
  4964.5 2163.40  4988.4 2163.31  4991.7 2161.12  4992.2 2160.62  4997.8 2160.62
  4998.3 2161.12  5002.3 2162.08  5025.3 2174.35  5035.3 2177.94  5045.3 2179.61
  5055.3 2180.30  5085.3 2178.94  5095.3 2179.73  5100.3 2179.27  5105.3 2179.04
#Mann=6,-1,0
  4544.7    0.07       0  4901.5    0.16       0  4991.7    0.07       0
  4998.3    0.16       0  5002.3    0.07       0  5100.3   0.035       0
Bank Sta=4991.7,4998.3
Exp/Cntr=0.3,0.1