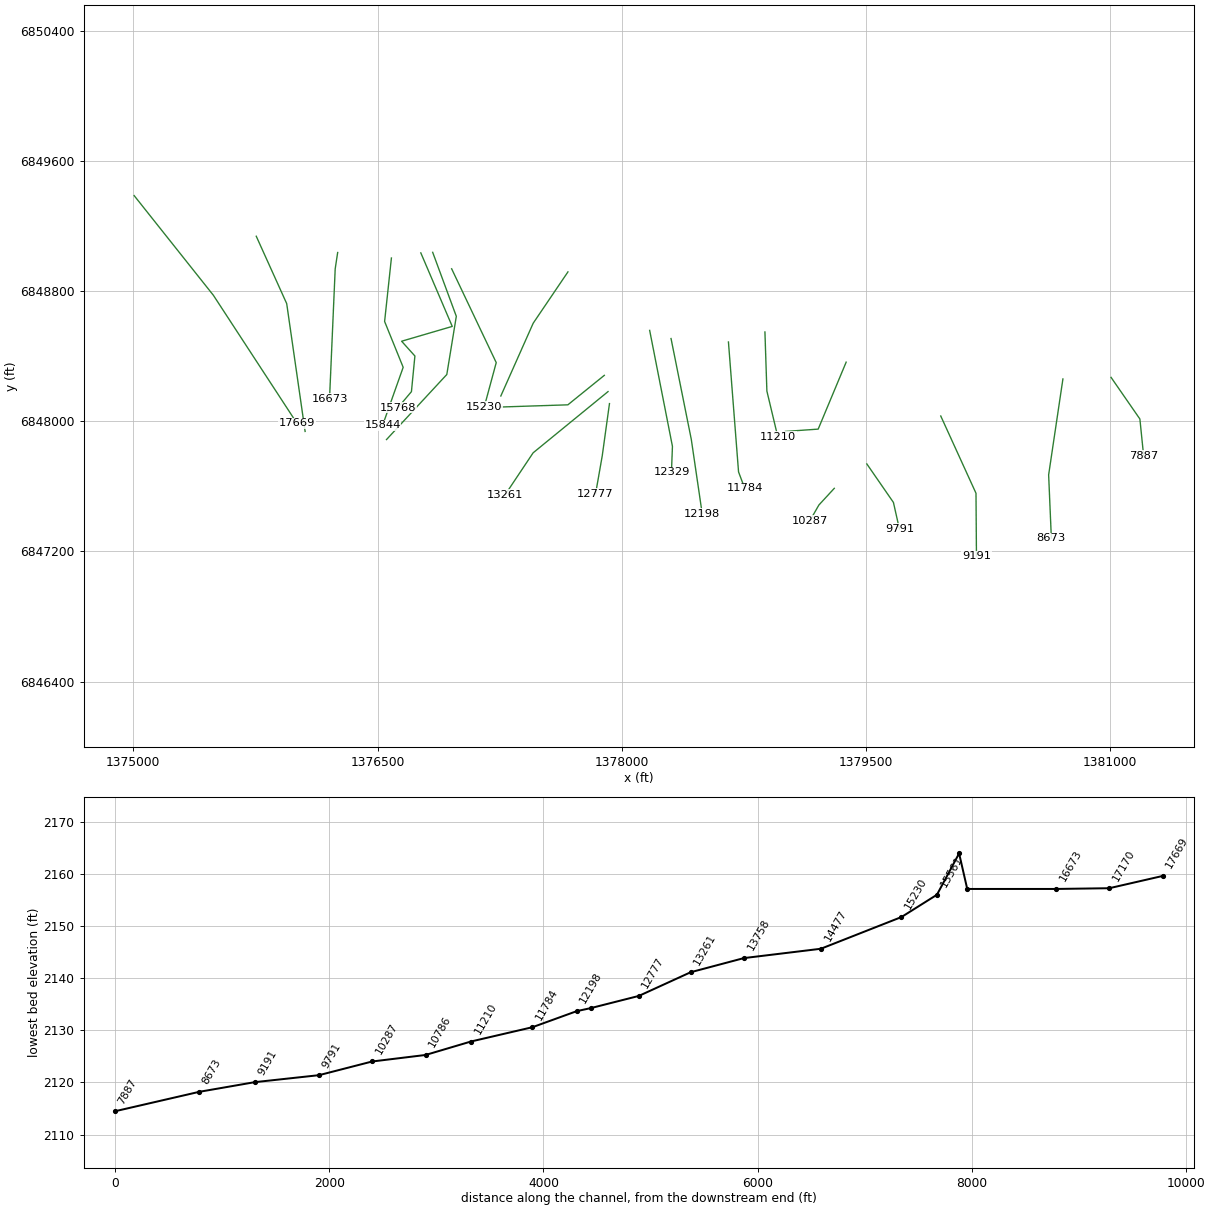
HEC-RAS study Sweetwater Creek Trib 21.prj: Sweetwater Creek Trib 21 Base Level Engineering

--- Sweetwater Creek Trib 21.g01 (geometry) --- (continued)

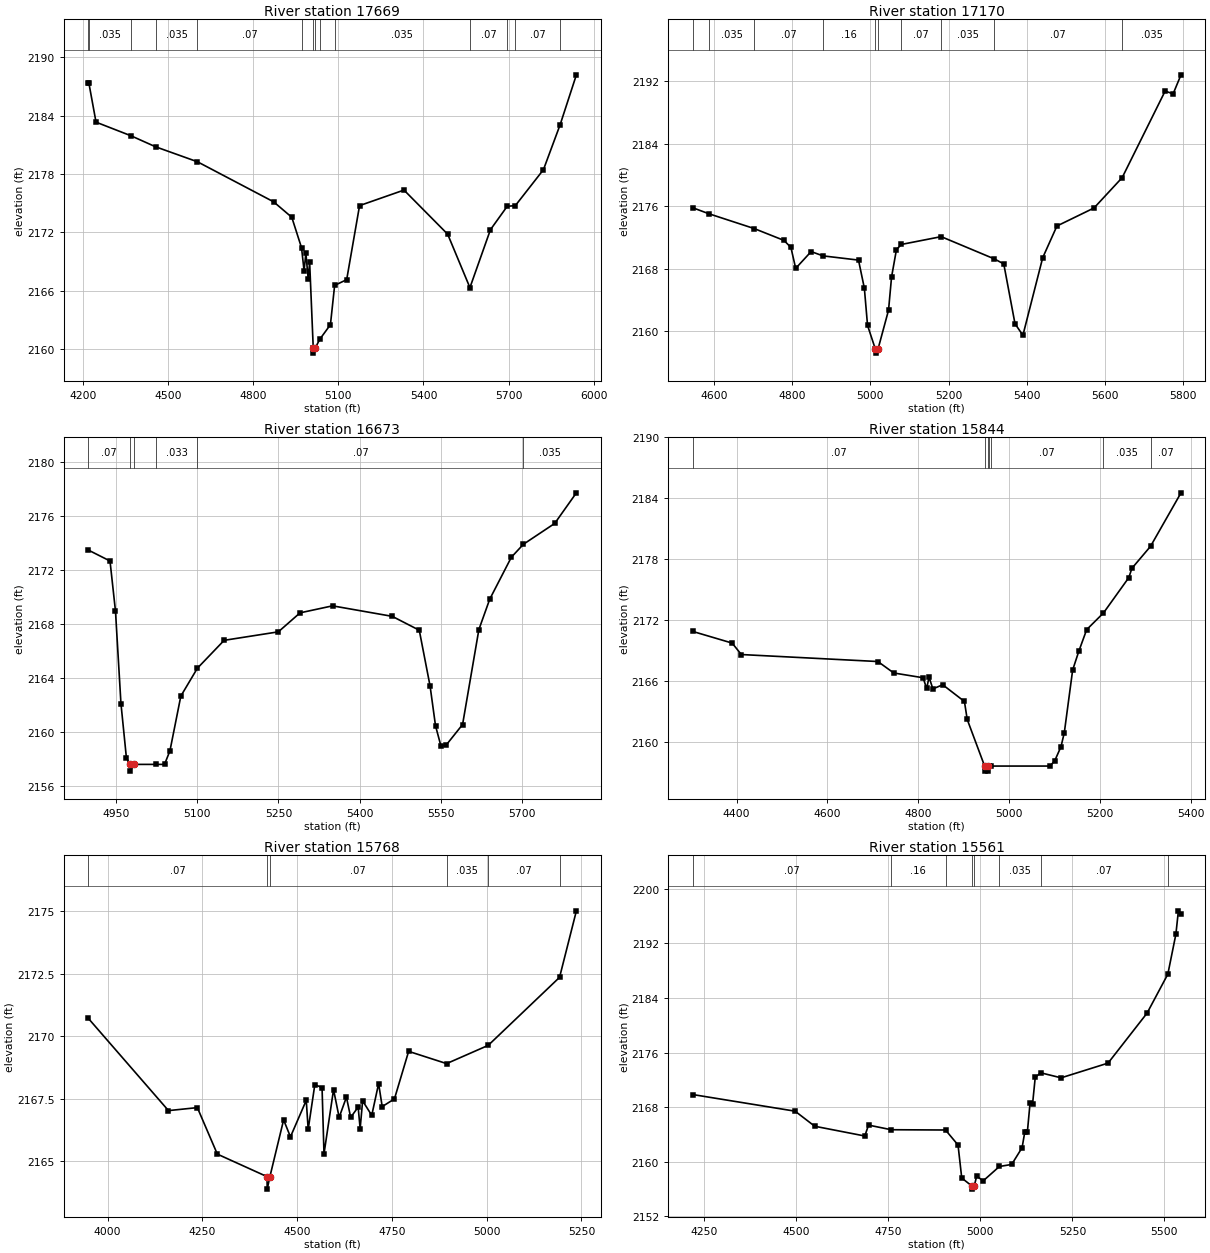
Type RM Length L Ch R = 1,17669,499,499,499
BEGIN DESCRIPTION:
Sweetwater Creek Trib 21 31.0
END DESCRIPTION:
XS GIS Cut Line= 3
      1375005.00      6849388.00      1375491.80      6848774.85
      1376004.99      6847988.02
#Sta/Elev= 30
  4217.1 2187.35  4220.0 2187.35  4245.1 2183.34  4369.0 2181.93  4455.6 2180.80
  4603.0 2179.26  4871.6 2175.14  4935.6 2173.55  4970.0 2170.41  4978.9 2168.05
  4985.3 2169.86  4993.4 2167.22  4998.6 2168.91  5011.3 2160.07  5011.8 2159.57
  5017.9 2160.07  5034.2 2160.99  5071.9 2162.50  5086.7 2166.54  5129.2 2167.13
  5174.6 2174.75  5331.3 2176.35  5485.4 2171.81  5563.9 2166.31  5636.2 2172.27
  5695.4 2174.68  5724.1 2174.75  5823.2 2178.45  5882.1 2183.08  5939.4 2188.21
#Mann=14,-1,0
  4217.1    0.07       0  4220.0   0.035       0  4369.0    0.07       0
  4455.6   0.035       0  4603.0    0.07       0  4970.0    0.16       0
  5011.3    0.07       0  5017.9    0.16       0  5034.2    0.07       0
  5086.7   0.035       0  5563.9    0.07       0  5695.4   0.035       0
  5724.1    0.07       0  5882.1   0.035       0
Bank Sta=5011.3,5017.9
Exp/Cntr=0.3,0.1

Type RM Length L Ch R = 1,17170,497,497,497
BEGIN DESCRIPTION:
Sweetwater Creek Trib 21 30.0
END DESCRIPTION:
XS GIS Cut Line= 3
      1375754.99      6849138.03      1375941.95      6848723.87
      1376055.01      6847937.96
#Sta/Elev= 30
  4545.6 2175.82  4586.9 2175.05  4702.5 2173.16  4779.0 2171.64  4796.7 2170.74
  4808.9 2168.06  4848.4 2170.21  4878.8 2169.66  4969.5 2169.12  4984.5 2165.52
  4992.6 2160.77  5012.7 2157.72  5013.2 2157.22  5019.3 2157.72  5046.3 2162.72
  5054.0 2166.95  5066.5 2170.46  5078.9 2171.12  5180.9 2172.12  5316.9 2169.27
  5340.9 2168.63  5369.6 2160.98  5389.8 2159.50  5440.4 2169.42  5476.8 2173.48
  5571.7 2175.79  5643.6 2179.67  5753.5 2190.75  5773.8 2190.38  5794.0 2192.82
#Mann=10,-1,0
  4545.6    0.07       0  4586.9   0.035       0  4702.5    0.07       0
  4878.8    0.16       0  5012.7    0.07       0  5019.3    0.16       0
  5078.9    0.07       0  5180.9   0.035       0  5316.9    0.07       0
  5643.6   0.035       0
Bank Sta=5012.7,5019.3
Exp/Cntr=0.3,0.1

Type RM Length L Ch R = 1,16673,829,829,829
BEGIN DESCRIPTION:
Sweetwater Creek Trib 21 29.0
END DESCRIPTION:
XS GIS Cut Line= 3
      1376255.01      6849038.04      1376239.79      6848937.49
      1376205.00      6848138.05
#Sta/Elev= 30
  4898.3 2173.50  4938.8 2172.68  4948.9 2168.96  4959.0 2162.10  4969.1 2158.06
  4975.9 2157.58  4976.4 2157.08  4982.6 2157.58  5023.2 2157.58  5039.5 2157.58
  5049.5 2158.59  5069.6 2162.65  5100.2 2164.72  5149.6 2166.79  5249.7 2167.42
  5289.8 2168.83  5349.8 2169.35  5460.1 2168.57  5510.0 2167.54  5530.0 2163.39
  5540.0 2160.45  5550.0 2158.95  5560.0 2159.03  5590.0 2160.54  5620.1 2167.59
  5640.1 2169.84  5680.1 2172.96  5702.3 2173.92  5760.2 2175.47  5800.2 2177.74
#Mann=6,-1,0
  4898.3    0.07       0  4975.9    0.07       0  4982.6    0.07       0
  5023.2   0.033       0  5100.2    0.07       0  5702.3   0.035       0
Bank Sta=4975.9,4982.6
Exp/Cntr=0.3,0.1

Type RM Length L Ch R = 1,15844,76,76,76
BEGIN DESCRIPTION:
Sweetwater Creek Trib 21 4153
END DESCRIPTION:
XS GIS Cut Line= 4
      1376585.12      6849004.35      1376543.27      6848614.03
      1376657.31      6848332.19      1376531.20      6847976.06
#Sta/Elev= 30
  4303.4 2170.86  4390.2 2169.71  4410.4 2168.58  4710.9 2167.89  4745.8 2166.76
  4810.3 2166.29  4818.1 2165.24  4823.5 2166.34  4831.9 2165.19  4853.5 2165.60
  4901.3 2163.95  4907.4 2162.18  4945.7 2157.58  4946.2 2157.08  4952.8 2157.08
  4953.3 2157.58  4954.5 2157.58  4958.7 2157.58  5089.3 2157.58  5099.9 2158.09
  5113.8 2159.50  5121.1 2160.89  5139.4 2167.05  5153.0 2168.91  5170.3 2171.04
  5207.2 2172.68  5263.0 2176.17  5269.7 2177.08  5310.7 2179.25  5377.8 2184.53
#Mann=7,-1,0
  4303.4    0.07       0  4945.7    0.07       0  4953.3    0.07       0
  4954.5   0.033       0  4958.7    0.07       0  5207.2   0.035       0
  5310.7    0.07       0
Bank Sta=4945.7,4953.3
Exp/Cntr=0.3,0.1

Type RM Length L Ch R = 1,15768,207,207,207
BEGIN DESCRIPTION:
Sweetwater Creek Trib 21 4154
END DESCRIPTION:
XS GIS Cut Line= 6
      1376765.69      6849035.64      1376958.71      6848583.68
      1376647.73      6848492.53      1376729.32      6848401.82
      1376708.06      6848182.64      1376624.39      6848082.93
#Sta/Elev= 30
  3948.5 2170.73  4160.6 2167.03  4236.8 2167.15  4289.5 2165.29  4420.6 2164.39
  4421.1 2163.89  4428.2 2164.39  4464.4 2166.66  4482.4 2165.98  4524.1 2167.44
  4529.2 2166.28  4546.7 2168.07  4565.8 2167.95  4570.9 2165.30  4596.1 2167.87
  4610.9 2166.76  4630.1 2167.57  4641.3 2166.76  4661.0 2167.17  4666.3 2166.31
  4672.8 2167.42  4696.9 2166.84  4715.0 2168.11  4724.5 2167.19  4756.8 2167.50
  4794.2 2169.40  4894.4 2168.91  5004.2 2169.64  5192.4 2172.36  5236.8 2175.02
#Mann=6,-1,0
  3948.5    0.07       0  4420.6   0.035       0  4428.2    0.07       0
  4894.4   0.035       0  5004.2    0.07       0  5192.4   0.035       0
Bank Sta=4420.6,4428.2
Exp/Cntr=0.3,0.1

Type RM Length L Ch R = 1,15561,331,331,331
BEGIN DESCRIPTION:
Sweetwater Creek Trib 21 28.0
END DESCRIPTION:
XS GIS Cut Line= 4
      1376838.59      6849039.15      1376983.68      6848645.71
      1376925.29      6848287.99      1376554.98      6847887.98
#Sta/Elev= 30
  4218.2 2169.84  4496.5 2167.40  4549.8 2165.19  4685.9 2163.76  4696.0 2165.36
  4757.6 2164.68  4905.2 2164.64  4939.2 2162.44  4949.3 2157.60  4975.9 2156.47
  4976.4 2155.97  4983.5 2156.47  4989.9 2157.89  5007.3 2157.17  5051.6 2159.29
  5085.0 2159.59  5113.3 2162.05  5120.7 2164.38  5127.5 2164.28  5134.9 2168.57
  5141.7 2168.42  5149.0 2172.36  5163.8 2173.03  5219.3 2172.29  5346.9 2174.45
  5452.9 2181.78  5509.3 2187.49  5531.2 2193.35  5538.0 2196.78  5545.1 2196.34
#Mann=8,-1,0
  4218.2    0.07       0  4757.6    0.16       0  4905.2    0.07       0
  4975.9    0.07       0  4983.5    0.07       0  5051.6   0.035       0
  5163.8    0.07       0  5509.3   0.035       0
Bank Sta=4975.9,4983.5
Exp/Cntr=0.3,0.1

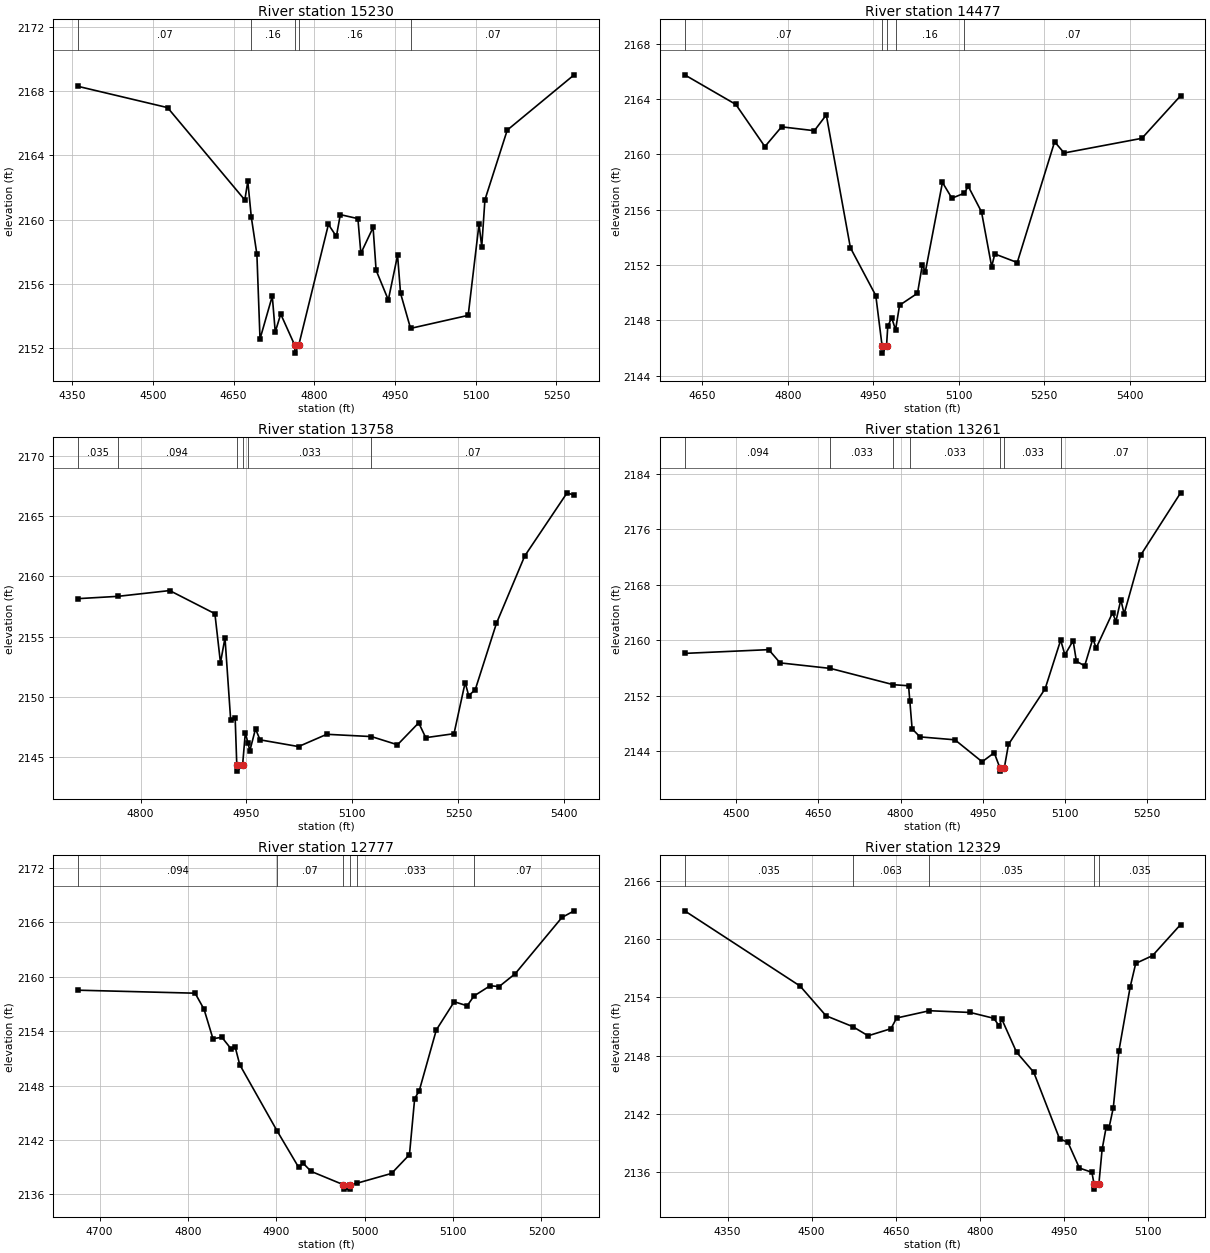
Type RM Length L Ch R = 1,15230,753,753,753
BEGIN DESCRIPTION:
Sweetwater Creek Trib 21 27.0
END DESCRIPTION:
XS GIS Cut Line= 3
      1376955.02      6848937.96      1377228.86      6848361.06
      1377154.99      6848087.97
#Sta/Elev= 30
  4361.4 2168.30  4527.4 2166.98  4671.0 2161.23  4676.5 2162.40  4683.0 2160.17
  4693.4 2157.85  4699.2 2152.58  4722.0 2155.25  4727.5 2153.02  4737.7 2154.13
  4763.6 2152.20  4764.1 2151.70  4771.2 2152.20  4826.3 2159.71  4841.1 2158.96
  4848.4 2160.32  4881.1 2160.07  4886.6 2157.91  4909.3 2159.52  4914.9 2156.86
  4937.6 2155.01  4954.8 2157.79  4960.3 2155.43  4978.9 2153.24  5086.0 2154.05
  5106.1 2159.72  5111.2 2158.33  5117.1 2161.24  5158.6 2165.58  5282.9 2169.02
#Mann=5,-1,0
  4361.4    0.07       0  4683.0    0.16       0  4763.6    0.07       0
  4771.2    0.16       0  4978.9    0.07       0
Bank Sta=4763.6,4771.2
Exp/Cntr=0.3,0.1

Type RM Length L Ch R = 1,14477,719,719,719
BEGIN DESCRIPTION:
Sweetwater Creek Trib 21 26.1
END DESCRIPTION:
XS GIS Cut Line= 3
      1377669.30      6848918.93      1377455.90      6848603.42
      1377257.09      6848155.89
#Sta/Elev= 30
  4619.1 2165.74  4708.9 2163.60  4759.9 2160.55  4789.2 2161.98  4846.7 2161.70
  4867.7 2162.84  4910.0 2153.24  4954.6 2149.78  4965.7 2146.12  4966.2 2145.62
  4973.4 2146.12  4975.6 2147.55  4982.4 2148.19  4989.3 2147.30  4996.3 2149.08
  5027.8 2149.95  5036.2 2151.98  5041.7 2151.52  5071.6 2157.96  5088.2 2156.82
  5109.8 2157.18  5116.9 2157.68  5140.2 2155.83  5158.0 2151.87  5163.5 2152.79
  5202.9 2152.17  5268.5 2160.90  5285.2 2160.09  5421.7 2161.15  5489.7 2164.23
#Mann=5,-1,0
  4619.1    0.07       0  4965.7    0.07       0  4973.4    0.07       0
  4989.3    0.16       0  5109.8    0.07       0
Bank Sta=4965.7,4973.4
Exp/Cntr=0.3,0.1

Type RM Length L Ch R = 1,13758,497,497,497
BEGIN DESCRIPTION:
Sweetwater Creek Trib 21 26.0
END DESCRIPTION:
XS GIS Cut Line= 3
      1377892.72      6848282.81      1377668.71      6848101.48
      1377255.03      6848088.00
#Sta/Elev= 30
  4711.8 2158.16  4768.0 2158.35  4841.3 2158.83  4905.3 2156.91  4913.2 2152.83
  4919.6 2154.90  4927.6 2148.11  4934.0 2148.22  4936.3 2144.33  4936.8 2143.83
  4944.5 2144.33  4948.4 2147.03  4952.0 2146.19  4954.8 2145.53  4962.8 2147.34
  4969.2 2146.43  5023.7 2145.87  5063.7 2146.89  5127.0 2146.70  5163.8 2146.02
  5193.8 2147.84  5203.8 2146.61  5243.8 2146.94  5259.6 2151.19  5264.6 2150.10
  5273.9 2150.60  5303.9 2156.11  5343.9 2161.70  5403.9 2166.95  5413.9 2166.75
#Mann=6,-1,0
  4711.8   0.035       0  4768.0   0.094       0  4936.3   0.033       0
  4944.5   0.094       0  4952.0   0.033       0  5127.0    0.07       0
Bank Sta=4936.3,4944.5
Exp/Cntr=0.3,0.1

Type RM Length L Ch R = 1,13261,484,484,484
BEGIN DESCRIPTION:
Sweetwater Creek Trib 21 25.0
END DESCRIPTION:
XS GIS Cut Line= 3
      1377915.54      6848182.89      1377455.51      6847806.47
      1377282.68      6847547.19
#Sta/Elev= 30
  4405.6 2158.11  4559.1 2158.65  4579.9 2156.74  4671.9 2155.94  4786.9 2153.59
  4814.6 2153.44  4816.9 2151.24  4821.1 2147.22  4835.5 2146.06  4899.3 2145.64
  4949.0 2142.47  4971.1 2143.77  4981.3 2141.62  4981.8 2141.12  4989.6 2141.62
  4997.1 2144.97  5064.1 2153.01  5092.5 2160.03  5100.2 2157.90  5115.2 2159.94
  5121.2 2156.98  5136.3 2156.31  5151.3 2160.24  5157.3 2158.87  5187.3 2163.99
  5193.3 2162.70  5202.4 2165.86  5208.4 2163.81  5238.4 2172.25  5311.6 2181.28
#Mann=7,-1,0
  4405.6   0.094       0  4671.9   0.033       0  4786.9    0.07       0
  4816.9   0.033       0  4981.3   0.033       0  4989.6   0.033       0
  5092.5    0.07       0
Bank Sta=4981.3,4989.6
Exp/Cntr=0.3,0.1

Type RM Length L Ch R = 1,12777,448,448,448
BEGIN DESCRIPTION:
Sweetwater Creek Trib 21 24.0
END DESCRIPTION:
XS GIS Cut Line= 3
      1377924.35      6848109.05      1377879.90      6847787.81
      1377838.99      6847554.37
#Sta/Elev= 30
  4675.7 2158.51  4808.0 2158.18  4818.1 2156.41  4828.2 2153.16  4838.3 2153.32
  4848.4 2152.08  4853.4 2152.23  4858.5 2150.30  4900.6 2143.03  4925.2 2138.98
  4930.3 2139.43  4939.2 2138.54  4975.5 2137.08  4976.0 2136.58  4983.3 2136.58
  4983.8 2137.08  4990.8 2137.22  5030.3 2138.31  5050.6 2140.38  5056.5 2146.57
  5061.6 2147.40  5081.0 2154.13  5101.3 2157.24  5115.9 2156.79  5123.6 2157.87
  5141.9 2159.00  5152.1 2158.91  5170.3 2160.33  5223.2 2166.53  5237.0 2167.26
#Mann=6,-1,0
  4675.7   0.094       0  4900.6    0.07       0  4975.5   0.033       0
  4983.8    0.07       0  4990.8   0.033       0  5123.6    0.07       0
Bank Sta=4975.5,4983.8
Exp/Cntr=0.3,0.1

Type RM Length L Ch R = 1,12329,131,131,131
BEGIN DESCRIPTION:
Sweetwater Creek Trib 21 23.0
END DESCRIPTION:
XS GIS Cut Line= 3
      1378171.17      6848559.15      1378311.05      6847846.15
      1378305.00      6847687.96
#Sta/Elev= 30
  4273.4 2162.89  4479.3 2155.15  4525.6 2152.09  4573.4 2150.97  4600.7 2150.03
  4641.4 2150.76  4651.6 2151.86  4710.2 2152.61  4782.9 2152.43  4824.9 2151.83
  4834.3 2151.07  4839.4 2151.72  4865.6 2148.34  4896.2 2146.28  4942.3 2139.43
  4957.3 2139.06  4977.7 2136.42  5000.0 2135.98  5003.9 2134.75  5004.4 2134.25
  5012.4 2134.75  5018.2 2138.33  5025.4 2140.61  5030.4 2140.52  5038.2 2142.63
  5048.2 2148.48  5068.2 2155.03  5078.2 2157.48  5108.2 2158.28  5158.3 2161.48
#Mann=5,-1,0
  4273.4   0.035       0  4573.4   0.063       0  4710.2   0.035       0
  5003.9   0.035       0  5012.4   0.035       0
Bank Sta=5003.9,5012.4
Exp/Cntr=0.3,0.1

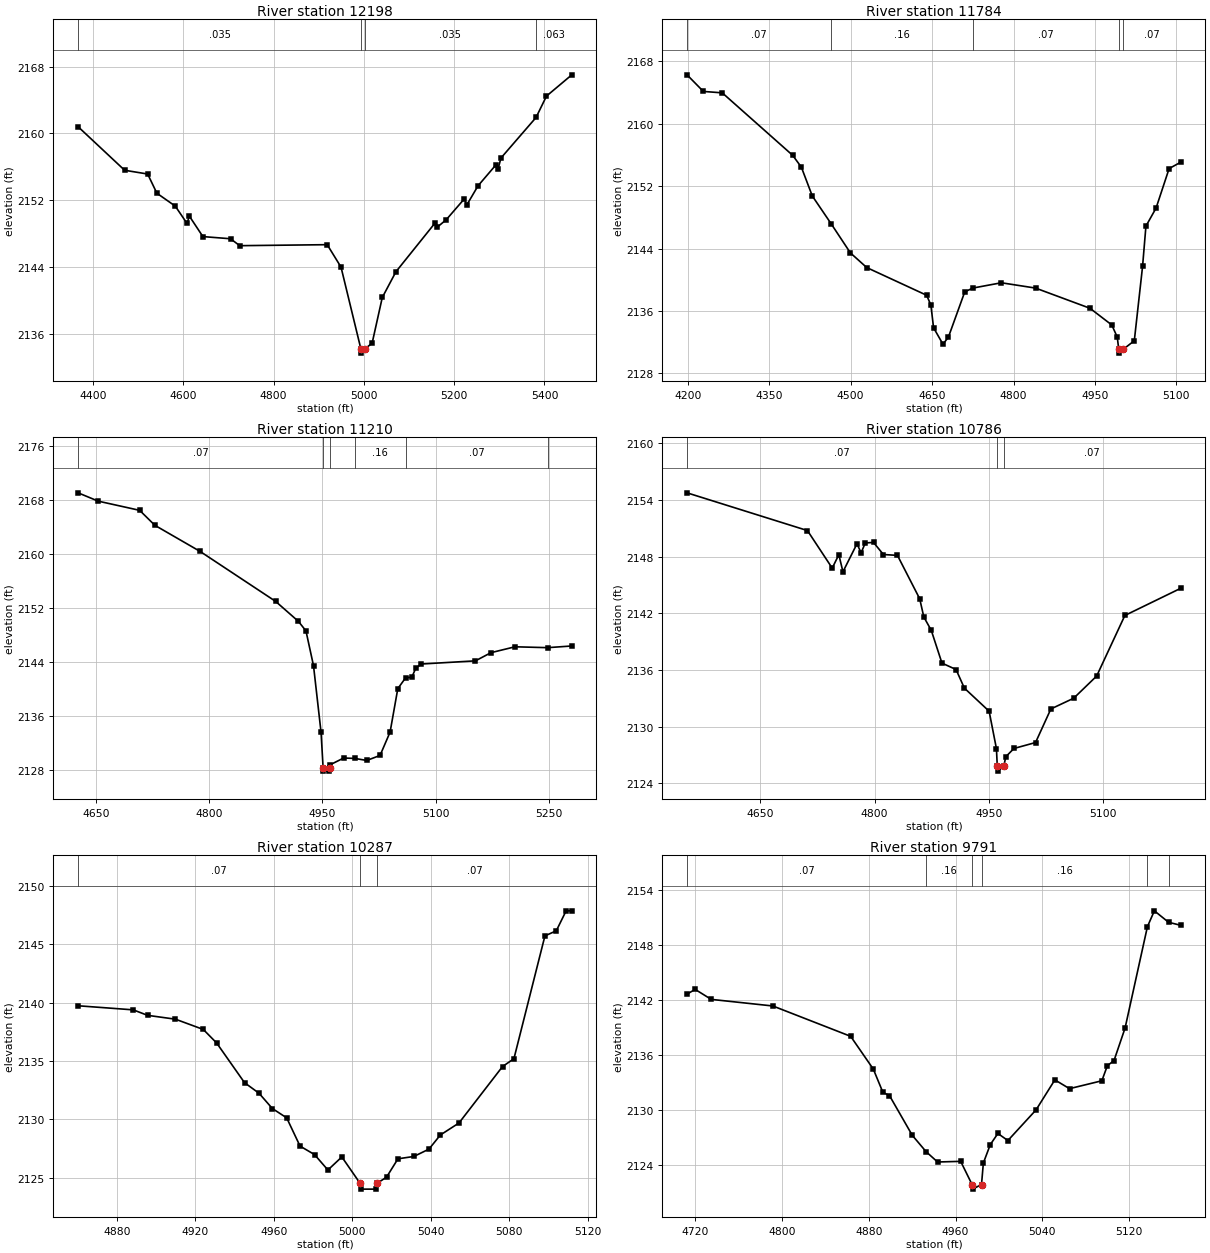
Type RM Length L Ch R = 1,12198,414,414,414
BEGIN DESCRIPTION:
Sweetwater Creek Trib 21 22.1
END DESCRIPTION:
XS GIS Cut Line= 3
      1378302.42      6848509.08      1378426.97      6847888.25
      1378493.82      6847432.53
#Sta/Elev= 30
  4366.8 2160.81  4469.9 2155.59  4520.9 2155.14  4541.3 2152.84  4582.1 2151.29
  4608.1 2149.22  4613.2 2150.10  4643.3 2147.64  4704.5 2147.38  4724.9 2146.55
  4918.7 2146.67  4949.3 2143.98  4993.3 2134.17  4993.8 2133.67  5001.8 2134.17
  5018.2 2134.86  5040.7 2140.34  5071.0 2143.43  5157.8 2149.28  5162.9 2148.79
  5182.2 2149.65  5222.6 2152.17  5227.6 2151.40  5252.9 2153.73  5292.4 2156.23
  5297.5 2155.78  5303.5 2157.05  5381.4 2161.92  5404.5 2164.48  5460.6 2167.03
#Mann=4,-1,0
  4366.8   0.035       0  4993.3   0.035       0  5001.8   0.035       0
  5381.4   0.063       0
Bank Sta=4993.3,5001.8
Exp/Cntr=0.3,0.1

Type RM Length L Ch R = 1,11784,574,574,574
BEGIN DESCRIPTION:
Sweetwater Creek Trib 21 22.0
END DESCRIPTION:
XS GIS Cut Line= 3
      1378655.00      6848487.99      1378717.06      6847689.10
      1378755.01      6847587.98
#Sta/Elev= 30
  4198.7 2166.27  4228.8 2164.14  4263.6 2163.96  4393.3 2155.95  4409.3 2154.43
  4429.4 2150.74  4464.2 2147.17  4499.6 2143.44  4529.7 2141.56  4640.0 2138.01
  4647.8 2136.76  4652.8 2133.84  4670.1 2131.73  4680.1 2132.64  4710.2 2138.44
  4725.0 2138.93  4777.6 2139.61  4840.6 2138.93  4940.9 2136.34  4981.0 2134.20
  4991.1 2132.65  4993.8 2131.09  4994.3 2130.59  5002.3 2131.09  5022.5 2132.18
  5037.7 2141.70  5043.9 2146.87  5062.6 2149.19  5086.6 2154.25  5108.0 2155.07
#Mann=5,-1,0
  4198.7    0.07       0  4464.2    0.16       0  4725.0    0.07       0
  4993.8    0.07       0  5002.3    0.07       0
Bank Sta=4993.8,5002.3
Exp/Cntr=0.3,0.1

Type RM Length L Ch R = 1,11210,424,424,424
BEGIN DESCRIPTION:
Sweetwater Creek Trib 21 21.0
END DESCRIPTION:
XS GIS Cut Line= 3
      1378879.12      6848549.51      1378891.08      6848186.14
      1378958.41      6847903.92
#Sta/Elev= 30
  4626.7 2169.01  4653.3 2167.78  4708.2 2166.42  4728.3 2164.21  4788.3 2160.34
  4888.3 2152.95  4918.4 2150.00  4928.4 2148.59  4938.4 2143.44  4948.4 2133.58
  4951.1 2128.35  4951.6 2127.85  4959.2 2127.85  4959.7 2128.35  4960.4 2128.79
  4978.4 2129.79  4992.9 2129.73  5008.9 2129.43  5026.5 2130.17  5039.8 2133.63
  5050.0 2140.05  5060.2 2141.63  5068.6 2141.76  5073.8 2143.06  5080.9 2143.69
  5152.8 2144.16  5173.4 2145.37  5205.2 2146.24  5248.3 2146.11  5280.4 2146.36
#Mann=6,-1,0
  4626.7    0.07       0  4951.1    0.07       0  4959.7    0.07       0
  4992.9    0.16       0  5060.2    0.07       0  5248.3   0.035       0
Bank Sta=4951.1,4959.7
Exp/Cntr=0.3,0.1

Type RM Length L Ch R = 1,10786,499,499,499
BEGIN DESCRIPTION:
Sweetwater Creek Trib 21 20.0
END DESCRIPTION:
XS GIS Cut Line= 3
      1379377.95      6848363.83      1379206.18      6847952.13
      1379004.98      6847938.00
#Sta/Elev= 30
  4553.9 2154.77  4711.9 2150.77  4744.4 2146.79  4753.1 2148.21  4758.5 2146.40
  4776.9 2149.37  4782.3 2148.41  4787.8 2149.46  4798.6 2149.51  4811.6 2148.23
  4830.0 2148.14  4859.2 2143.54  4864.6 2141.61  4874.4 2140.19  4888.4 2136.72
  4906.9 2136.04  4917.8 2134.07  4950.3 2131.62  4959.9 2127.64  4961.0 2125.77
  4961.5 2125.27  4969.6 2125.77  4972.0 2126.78  4982.8 2127.67  5011.2 2128.30
  5031.3 2131.86  5061.3 2133.00  5091.4 2135.35  5128.4 2141.77  5201.7 2144.65
#Mann=3,-1,0
  4553.9    0.07       0  4961.0    0.07       0  4969.6    0.07       0
Bank Sta=4961,4969.6
Exp/Cntr=0.3,0.1

Type RM Length L Ch R = 1,10287,496,496,496
BEGIN DESCRIPTION:
Sweetwater Creek Trib 21 19.0
END DESCRIPTION:
XS GIS Cut Line= 3
      1379305.00      6847588.00      1379210.34      6847485.26
      1379155.00      6847388.00
#Sta/Elev= 30
  4860.3 2139.74  4888.4 2139.39  4895.7 2138.92  4909.9 2138.59  4924.1 2137.71
  4930.9 2136.55  4945.1 2133.15  4952.5 2132.24  4959.3 2130.93  4966.6 2130.13
  4973.4 2127.71  4980.8 2126.98  4987.6 2125.66  4994.7 2126.78  5004.0 2124.52
  5004.5 2124.02  5012.2 2124.02  5012.7 2124.52  5017.5 2125.05  5023.3 2126.62
  5031.4 2126.82  5039.1 2127.45  5044.9 2128.66  5054.4 2129.69  5076.6 2134.53
  5082.4 2135.20  5098.2 2145.73  5104.0 2146.17  5109.0 2147.88  5111.9 2147.88
#Mann=3,-1,0
  4860.3    0.07       0  5004.0    0.07       0  5012.7    0.07       0
Bank Sta=5004,5012.7
Exp/Cntr=0.3,0.1

Type RM Length L Ch R = 1,9791,600,600,600
BEGIN DESCRIPTION:
Sweetwater Creek Trib 21 18.0
END DESCRIPTION:
XS GIS Cut Line= 3
      1379504.99      6847738.01      1379668.31      6847501.40
      1379705.01      6847337.97
#Sta/Elev= 30
  4712.5 2142.67  4720.0 2143.19  4734.8 2142.10  4791.6 2141.38  4863.3 2138.07
  4884.2 2134.49  4893.0 2131.96  4899.1 2131.60  4920.1 2127.27  4932.8 2125.49
  4943.4 2124.36  4964.7 2124.43  4975.2 2121.90  4975.7 2121.40  4983.9 2121.90
  4985.6 2124.25  4992.0 2126.26  4999.0 2127.47  5008.2 2126.70  5034.2 2130.05
  5051.5 2133.32  5065.0 2132.36  5094.8 2133.22  5099.9 2134.87  5106.0 2135.42
  5116.2 2138.97  5136.8 2150.03  5143.2 2151.76  5156.3 2150.51  5167.5 2150.18
#Mann=6,-1,0
  4712.5    0.07       0  4932.8    0.16       0  4975.2    0.07       0
  4983.9    0.16       0  5136.8    0.07       0  5156.3   0.035       0
Bank Sta=4975.2,4983.9
Exp/Cntr=0.3,0.1

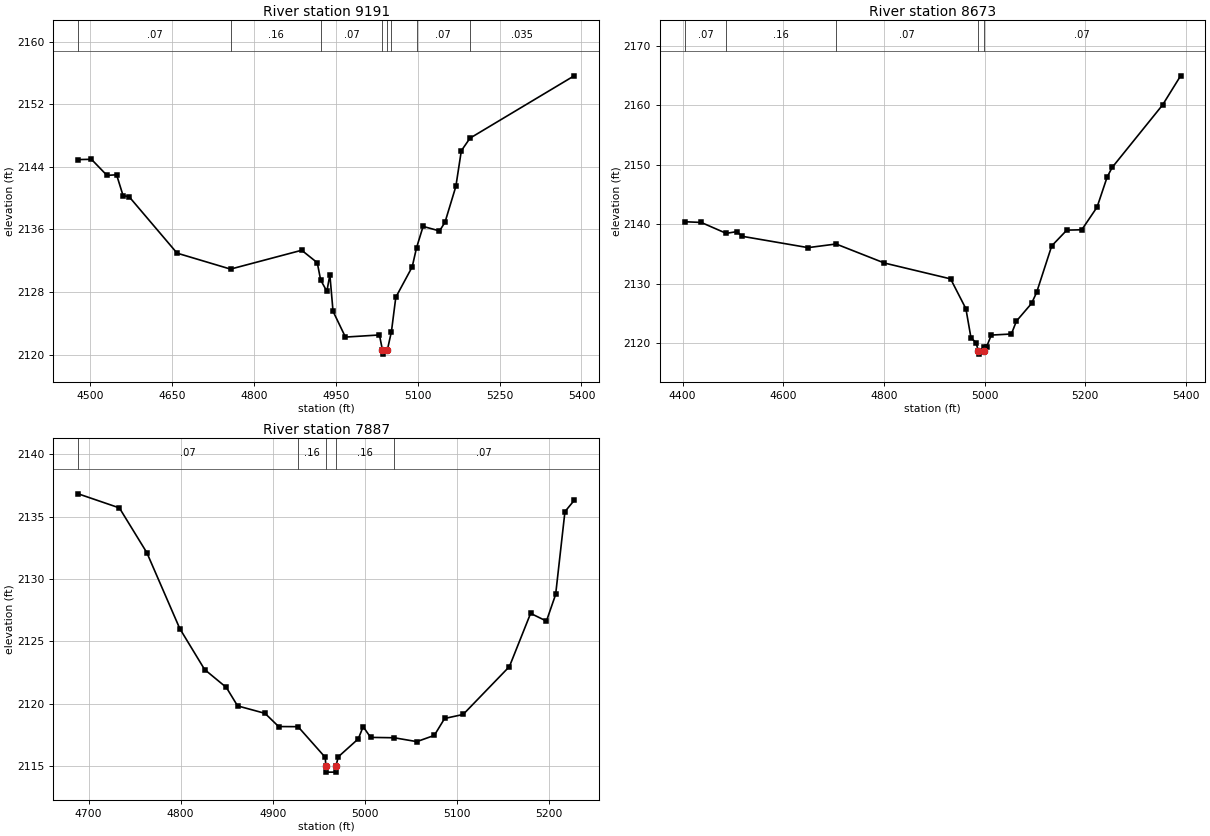
Type RM Length L Ch R = 1,9191,518,518,518
BEGIN DESCRIPTION:
Sweetwater Creek Trib 21 17.1
END DESCRIPTION:
XS GIS Cut Line= 3
      1379958.98      6848032.78      1380175.38      6847557.85
      1380178.22      6847171.26
#Sta/Elev= 30
  4478.1 2144.93  4502.3 2144.97  4530.8 2142.91  4548.4 2142.99  4560.3 2140.32
  4571.3 2140.19  4659.2 2132.97  4757.1 2130.93  4887.5 2133.34  4916.0 2131.75
  4922.2 2129.54  4933.6 2128.09  4939.1 2130.20  4944.9 2125.54  4967.6 2122.24
  5029.9 2122.51  5035.5 2120.56  5036.0 2120.06  5044.3 2120.56  5051.9 2122.95
  5059.9 2127.33  5089.9 2131.21  5097.9 2133.67  5109.9 2136.39  5139.9 2135.81
  5149.9 2136.90  5169.9 2141.50  5179.9 2146.06  5195.8 2147.67  5386.6 2155.64
#Mann=8,-1,0
  4478.1    0.07       0  4757.1    0.16       0  4922.2    0.07       0
  5035.5    0.07       0  5044.3    0.07       0  5051.9    0.16       0
  5097.9    0.07       0  5195.8   0.035       0
Bank Sta=5035.5,5044.3
Exp/Cntr=0.3,0.1

Type RM Length L Ch R = 1,8673,786,786,786
BEGIN DESCRIPTION:
Sweetwater Creek Trib 21 16.0
END DESCRIPTION:
XS GIS Cut Line= 3
      1380709.23      6848260.57      1380621.55      6847671.06
      1380638.20      6847282.11
#Sta/Elev= 30
  4404.0 2140.45  4436.9 2140.33  4486.5 2138.50  4507.7 2138.79  4517.8 2138.01
  4649.2 2136.10  4704.8 2136.71  4800.9 2133.51  4932.3 2130.85  4962.7 2125.84
  4972.8 2120.95  4982.9 2120.14  4987.4 2118.71  4987.9 2118.21  4998.5 2118.71
  4999.0 2119.47  5004.0 2119.47  5013.1 2121.41  5053.1 2121.59  5063.1 2123.76
  5093.1 2126.72  5103.2 2128.57  5133.2 2136.39  5163.2 2139.04  5192.9 2139.10
  5223.3 2142.90  5243.3 2147.95  5253.3 2149.57  5353.4 2160.06  5389.3 2164.96
#Mann=5,-1,0
  4404.0    0.07       0  4486.5    0.16       0  4704.8    0.07       0
  4987.4    0.07       0  4998.5    0.07       0
Bank Sta=4987.4,4998.5
Exp/Cntr=0.3,0.1

Type RM Length L Ch R = 1,7887,529,529,529
BEGIN DESCRIPTION:
Sweetwater Creek Trib 21 15.0
END DESCRIPTION:
XS GIS Cut Line= 3
      1381004.93      6848270.31      1381181.95      6848014.36
      1381205.00      6847788.03
#Sta/Elev= 30
  4688.8 2136.84  4733.5 2135.71  4763.3 2132.12  4799.1 2126.02  4826.1 2122.73
  4849.7 2121.29  4861.9 2119.81  4891.7 2119.21  4906.5 2118.15  4927.6 2118.14
  4957.2 2115.67  4957.7 2114.99  4958.2 2114.49  4968.3 2114.49  4968.8 2114.99
  4971.3 2115.72  4993.0 2117.16  4998.3 2118.14  5006.4 2117.28  5032.0 2117.25
  5056.6 2116.94  5075.6 2117.44  5086.8 2118.80  5106.9 2119.12  5157.2 2122.97
  5180.2 2127.24  5197.4 2126.62  5207.4 2128.76  5217.5 2135.41  5227.5 2136.31
#Mann=5,-1,0
  4688.8    0.07       0  4927.6    0.16       0  4957.7    0.07       0
  4968.8    0.16       0  5032.0    0.07       0
Bank Sta=4957.7,4968.8
Exp/Cntr=0.3,0.1