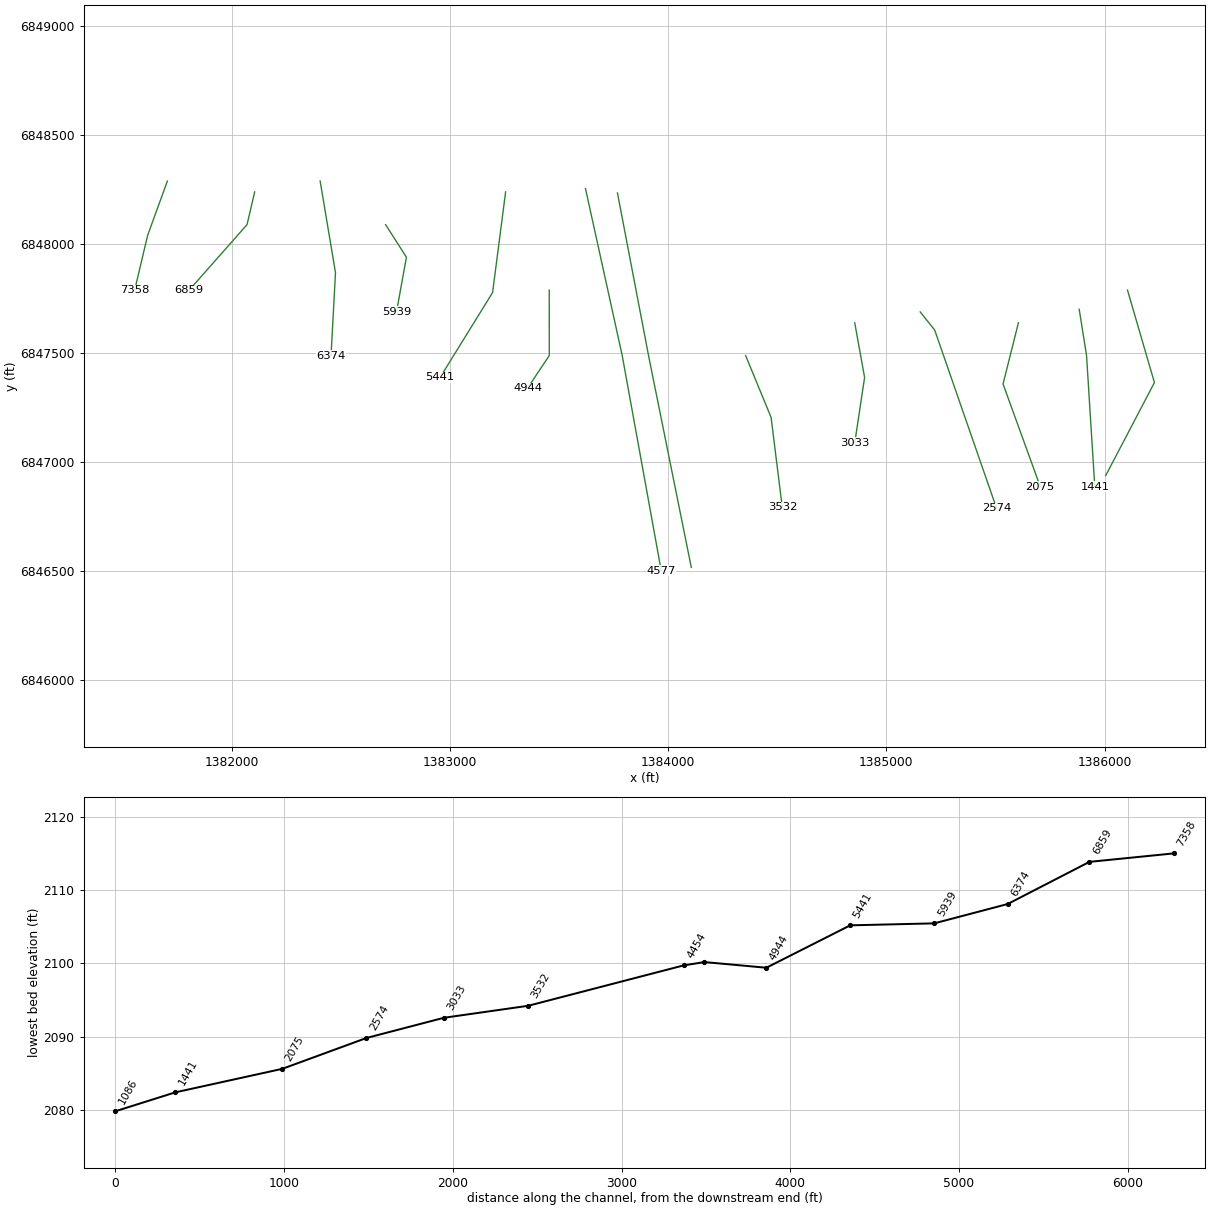
HEC-RAS study Sweetwater Creek Trib 21.prj: Sweetwater Creek Trib 21 Base Level Engineering

--- Sweetwater Creek Trib 21.g01 (geometry) --- (continued)

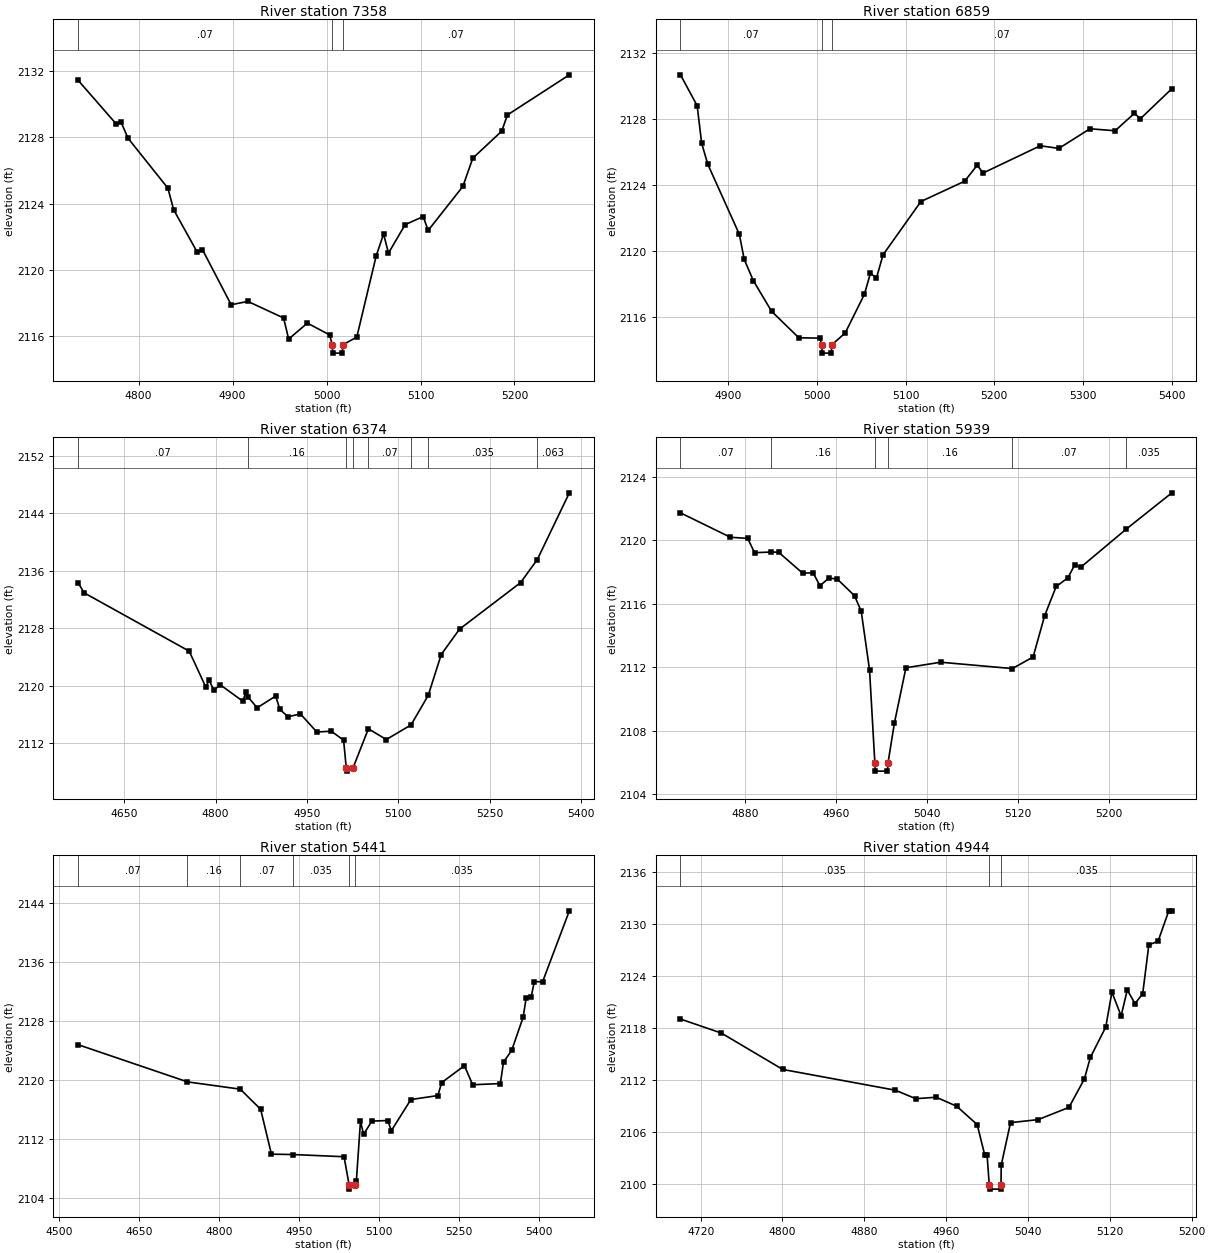
Type RM Length L Ch R = 1,7358,499,499,499
BEGIN DESCRIPTION:
Sweetwater Creek Trib 21 14.0
END DESCRIPTION:
XS GIS Cut Line= 3
      1381704.99      6848287.97      1381614.66      6848039.38
      1381554.99      6847787.96
#Sta/Elev= 30
  4735.5 2131.45  4776.1 2128.81  4781.4 2128.91  4788.7 2127.95  4831.2 2124.93
  4837.3 2123.63  4862.5 2121.06  4867.9 2121.23  4898.5 2117.90  4916.3 2118.10
  4954.3 2117.10  4959.7 2115.83  4979.6 2116.79  5003.3 2116.08  5006.1 2115.48
  5006.6 2114.98  5016.8 2114.98  5017.3 2115.48  5032.2 2115.95  5052.8 2120.84
  5060.7 2122.17  5065.9 2121.01  5083.6 2122.73  5102.9 2123.22  5108.1 2122.38
  5145.1 2125.04  5155.6 2126.74  5186.4 2128.37  5192.5 2129.35  5258.4 2131.77
#Mann=3,-1,0
  4735.5    0.07       0  5006.1    0.07       0  5017.3    0.07       0
Bank Sta=5006.1,5017.3
Exp/Cntr=0.3,0.1

Type RM Length L Ch R = 1,6859,485,485,485
BEGIN DESCRIPTION:
Sweetwater Creek Trib 21 13.0
END DESCRIPTION:
XS GIS Cut Line= 3
      1382105.01      6848238.04      1382070.06      6848088.17
      1381805.03      6847788.03
#Sta/Elev= 30
  4846.1 2130.70  4864.9 2128.83  4870.0 2126.55  4876.9 2125.28  4912.5 2121.03
  4918.0 2119.51  4928.3 2118.22  4948.8 2116.37  4979.6 2114.76  5003.5 2114.74
  5005.4 2114.33  5005.9 2113.83  5016.2 2113.83  5016.7 2114.33  5031.9 2115.05
  5053.6 2117.40  5060.4 2118.68  5067.1 2118.37  5074.6 2119.79  5117.3 2123.02
  5166.6 2124.25  5180.8 2125.22  5187.5 2124.75  5252.0 2126.40  5272.9 2126.24
  5308.0 2127.43  5336.4 2127.31  5358.2 2128.37  5364.9 2128.04  5400.4 2129.86
#Mann=3,-1,0
  4846.1    0.07       0  5005.4    0.07       0  5016.7    0.07       0
Bank Sta=5005.4,5016.7
Exp/Cntr=0.3,0.1

Type RM Length L Ch R = 1,6374,435,435,435
BEGIN DESCRIPTION:
Sweetwater Creek Trib 21 12.0
END DESCRIPTION:
XS GIS Cut Line= 3
      1382405.00      6848288.00      1382475.34      6847868.05
      1382455.00      6847488.00
#Sta/Elev= 30
  4574.2 2134.36  4584.3 2132.92  4756.7 2124.80  4784.1 2119.77  4789.1 2120.81
  4797.3 2119.34  4807.4 2120.13  4844.7 2117.83  4849.8 2119.09  4853.4 2118.41
  4868.2 2116.91  4898.7 2118.55  4905.4 2116.69  4918.9 2115.66  4939.2 2116.06
  4966.1 2113.54  4989.9 2113.65  5010.1 2112.40  5014.4 2108.59  5014.9 2108.09
  5025.8 2108.59  5050.8 2113.99  5080.2 2112.49  5120.8 2114.53  5149.0 2118.64
  5170.3 2124.33  5200.3 2127.86  5300.5 2134.34  5328.0 2137.56  5380.6 2146.85
#Mann=8,-1,0
  4574.2    0.07       0  4853.4    0.16       0  5014.4    0.07       0
  5025.8    0.16       0  5050.8    0.07       0  5120.8    0.16       0
  5149.0   0.035       0  5328.0   0.063       0
Bank Sta=5014.4,5025.8
Exp/Cntr=0.3,0.1

Type RM Length L Ch R = 1,5939,498,498,498
BEGIN DESCRIPTION:
Sweetwater Creek Trib 21 11.0
END DESCRIPTION:
XS GIS Cut Line= 3
      1382705.02      6848087.96      1382800.42      6847938.87
      1382754.99      6847687.95
#Sta/Elev= 30
  4823.0 2121.73  4866.9 2120.19  4882.1 2120.12  4888.1 2119.22  4902.7 2119.26
  4909.2 2119.25  4930.4 2117.93  4939.6 2117.95  4945.6 2117.14  4953.5 2117.62
  4960.8 2117.56  4976.0 2116.51  4981.9 2115.53  4989.2 2111.84  4993.9 2105.96
  4994.4 2105.46  5004.9 2105.46  5005.4 2105.96  5011.1 2108.50  5021.2 2111.97
  5051.7 2112.32  5114.8 2111.92  5133.0 2112.65  5143.2 2115.26  5153.3 2117.09
  5163.5 2117.63  5169.7 2118.46  5174.7 2118.29  5214.8 2120.70  5255.0 2122.99
#Mann=6,-1,0
  4823.0    0.07       0  4902.7    0.16       0  4993.9    0.07       0
  5005.4    0.16       0  5114.8    0.07       0  5214.8   0.035       0
Bank Sta=4993.9,5005.4
Exp/Cntr=0.3,0.1

Type RM Length L Ch R = 1,5441,497,497,497
BEGIN DESCRIPTION:
Sweetwater Creek Trib 21 10.0
END DESCRIPTION:
XS GIS Cut Line= 3
      1383254.99      6848237.96      1383195.35      6847777.10
      1382954.97      6847387.96
#Sta/Elev= 30
  4535.3 2124.82  4740.8 2119.76  4839.9 2118.77  4878.1 2116.03  4898.3 2109.94
  4939.0 2109.89  5034.6 2109.59  5044.3 2105.69  5044.8 2105.19  5055.8 2105.69
  5057.7 2106.32  5065.4 2114.40  5071.3 2112.63  5086.7 2114.43  5116.5 2114.51
  5123.4 2113.14  5160.0 2117.36  5210.5 2117.90  5217.9 2119.67  5260.5 2121.96
  5275.9 2119.37  5327.9 2119.53  5333.8 2122.44  5349.2 2124.05  5370.5 2128.51
  5376.3 2131.13  5385.8 2131.34  5391.7 2133.39  5407.1 2133.35  5457.4 2143.00
#Mann=6,-1,0
  4535.3    0.07       0  4740.8    0.16       0  4839.9    0.07       0
  4939.0   0.035       0  5044.3   0.035       0  5055.8   0.035       0
Bank Sta=5044.3,5055.8
Exp/Cntr=0.3,0.1

Type RM Length L Ch R = 1,4944,367,367,367
BEGIN DESCRIPTION:
Sweetwater Creek Trib 21 9.0
END DESCRIPTION:
XS GIS Cut Line= 3
      1383455.00      6847788.03      1383455.13      6847488.33
      1383355.01      6847338.02
#Sta/Elev= 30
  4700.3 2119.02  4740.3 2117.40  4800.3 2113.21  4910.3 2110.82  4930.3 2109.84
  4950.3 2110.01  4970.3 2108.97  4990.3 2106.86  4997.7 2103.35  5000.0 2103.35
  5002.1 2099.92  5002.6 2099.42  5013.1 2099.42  5013.6 2099.92  5013.8 2102.19
  5022.9 2107.08  5049.9 2107.43  5080.0 2108.84  5095.0 2112.09  5101.0 2114.61
  5116.0 2118.10  5122.0 2122.12  5131.0 2119.38  5137.0 2122.36  5144.6 2120.80
  5152.1 2121.95  5158.1 2127.57  5167.1 2127.98  5177.6 2131.49  5180.6 2131.49
#Mann=3,-1,0
  4700.3   0.035       0  5002.1   0.035       0  5013.6   0.035       0
Bank Sta=5002.1,5013.6
Exp/Cntr=0.3,0.1

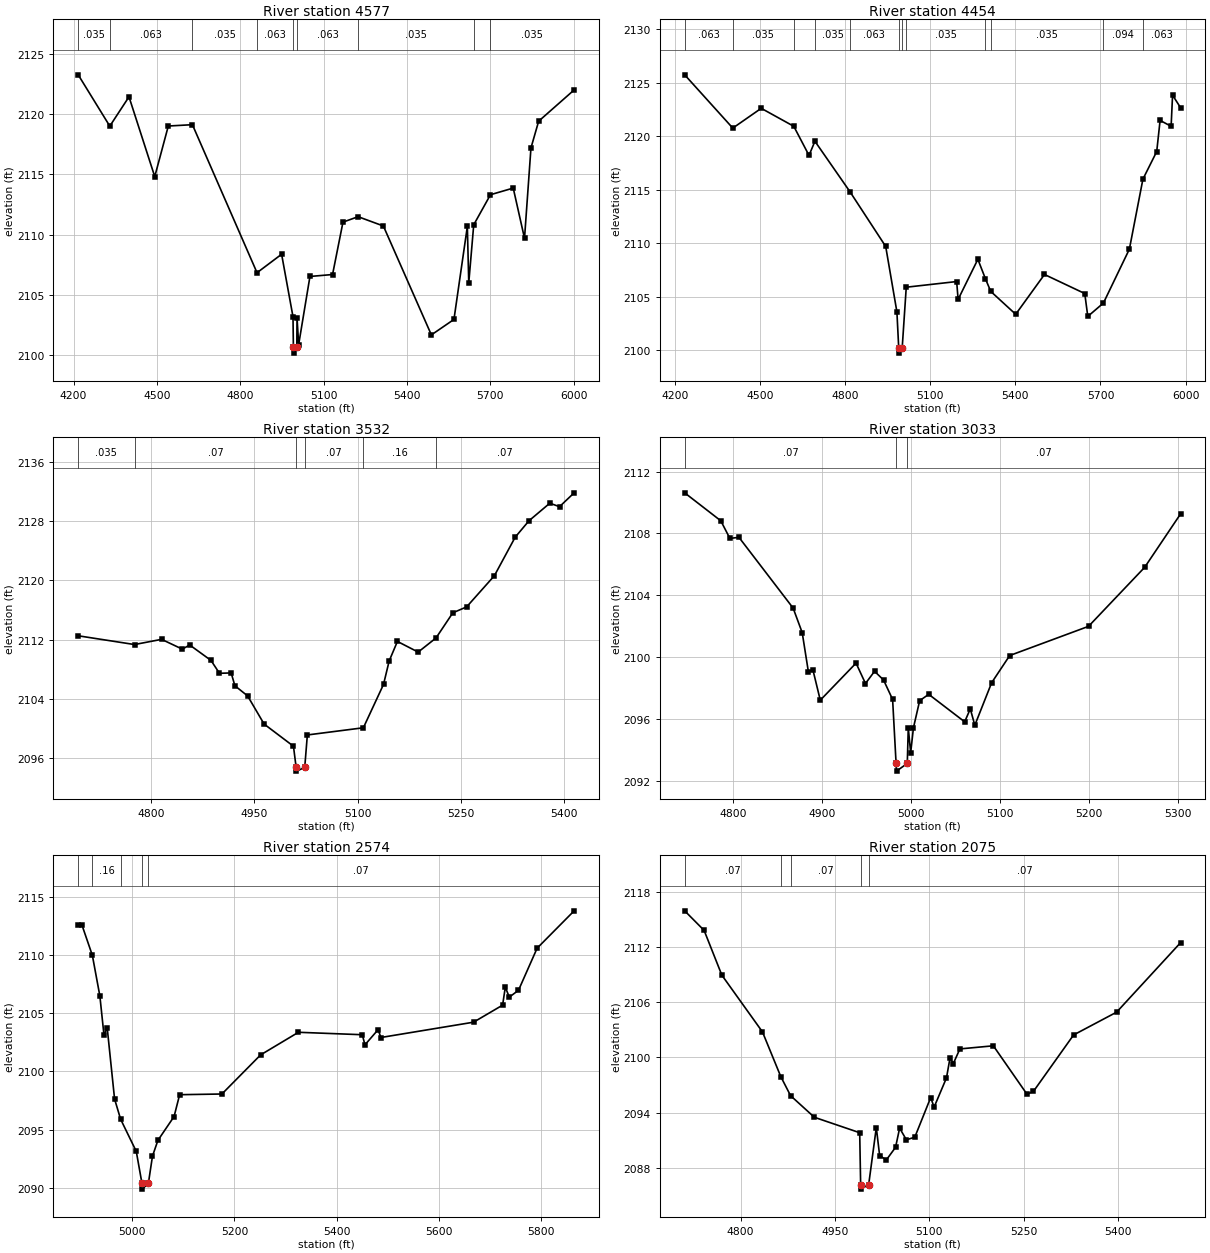
Type RM Length L Ch R = 1,4577,123,123,123
BEGIN DESCRIPTION:
Sweetwater Creek Trib 21 8.0
END DESCRIPTION:
XS GIS Cut Line= 3
      1383621.06      6848253.14      1383789.33      6847488.24
      1383968.17      6846502.21
#Sta/Elev= 30
  4216.8 2123.24  4330.5 2118.99  4399.6 2121.42  4492.3 2114.81  4541.1 2119.00
  4627.9 2119.11  4860.5 2106.85  4949.0 2108.38  4990.0 2103.20  4991.4 2100.69
  4991.9 2100.19  5003.7 2100.69  5004.5 2103.11  5010.4 2100.90  5051.0 2106.54
  5132.4 2106.70  5169.9 2111.04  5224.4 2111.49  5315.3 2110.72  5488.1 2101.70
  5569.4 2102.98  5617.6 2110.68  5622.7 2106.01  5640.6 2110.82  5700.8 2113.31
  5782.8 2113.86  5823.4 2109.70  5846.6 2117.18  5874.3 2119.40  6002.1 2121.99
#Mann=9,-1,0
  4216.8   0.035       0  4330.5   0.063       0  4627.9   0.035       0
  4860.5   0.063       0  4991.4   0.063       0  5003.7   0.063       0
  5224.4   0.035       0  5640.6   0.094       0  5700.8   0.035       0
Bank Sta=4991.4,5003.7
Exp/Cntr=0.3,0.1

Type RM Length L Ch R = 1,4454,922,922,922
BEGIN DESCRIPTION:
Sweetwater Creek Trib 21 7.0
END DESCRIPTION:
XS GIS Cut Line= 3
      1383767.54      6848233.18      1383911.52      6847480.33
      1384106.00      6846517.06
#Sta/Elev= 30
  4233.5 2125.75  4403.2 2120.77  4503.5 2122.62  4618.3 2120.94  4672.0 2118.22
  4692.9 2119.54  4816.6 2114.82  4942.5 2109.71  4982.0 2103.60  4988.4 2100.24
  4988.9 2099.74  5000.7 2100.24  5015.0 2105.90  5192.8 2106.43  5197.9 2104.76
  5267.6 2108.51  5294.4 2106.68  5313.0 2105.51  5401.0 2103.37  5502.5 2107.09
  5644.6 2105.31  5655.3 2103.17  5710.4 2104.42  5802.0 2109.46  5849.7 2116.00
  5898.4 2118.58  5910.3 2121.49  5949.2 2120.94  5954.3 2123.85  5982.7 2122.67
#Mann=12,-1,0
  4233.5   0.063       0  4403.2   0.035       0  4618.3   0.063       0
  4692.9   0.035       0  4816.6   0.063       0  4988.4   0.063       0
  5000.7   0.063       0  5015.0   0.035       0  5294.4    0.16       0
  5313.0   0.035       0  5710.4   0.094       0  5849.7   0.063       0
Bank Sta=4988.4,5000.7
Exp/Cntr=0.3,0.1

Type RM Length L Ch R = 1,3532,499,499,499
BEGIN DESCRIPTION:
Sweetwater Creek Trib 21 6.0
END DESCRIPTION:
XS GIS Cut Line= 3
      1384355.00      6847488.00      1384471.66      6847204.68
      1384522.75      6846792.83
#Sta/Elev= 30
  4693.6 2112.50  4775.5 2111.32  4814.9 2112.02  4845.0 2110.70  4855.8 2111.26
  4886.7 2109.18  4899.1 2107.44  4916.1 2107.49  4921.5 2105.76  4940.0 2104.39
  4964.0 2100.59  5006.7 2097.60  5010.6 2094.74  5011.1 2094.24  5023.1 2094.74
  5026.9 2099.12  5108.4 2100.09  5137.7 2105.94  5145.9 2109.10  5157.9 2111.74
  5188.1 2110.30  5214.1 2112.21  5238.5 2115.60  5258.6 2116.40  5299.0 2120.61
  5329.2 2125.80  5349.3 2128.02  5379.6 2130.39  5393.7 2129.92  5415.0 2131.79
#Mann=6,-1,0
  4693.6   0.035       0  4775.5    0.07       0  5010.6    0.07       0
  5023.1    0.07       0  5108.4    0.16       0  5214.1    0.07       0
Bank Sta=5010.6,5023.1
Exp/Cntr=0.3,0.1

Type RM Length L Ch R = 1,3033,459,459,459
BEGIN DESCRIPTION:
Sweetwater Creek Trib 21 5.0
END DESCRIPTION:
XS GIS Cut Line= 3
      1384855.00      6847638.00      1384900.11      6847387.73
      1384855.00      6847088.01
#Sta/Elev= 30
  4745.7 2110.62  4786.3 2108.81  4796.5 2107.67  4806.7 2107.74  4867.6 2103.16
  4877.8 2101.57  4884.7 2099.05  4889.8 2099.17  4898.1 2097.20  4938.3 2099.60
  4948.9 2098.28  4959.1 2099.07  4969.2 2098.51  4979.4 2097.25  4983.3 2093.11
  4983.8 2092.61  4995.9 2093.11  4997.0 2095.41  4999.7 2093.80  5002.8 2095.41
  5009.8 2097.17  5020.0 2097.58  5060.4 2095.80  5066.7 2096.64  5071.8 2095.58
  5090.7 2098.33  5111.0 2100.09  5199.6 2101.98  5262.7 2105.80  5303.1 2109.26
#Mann=3,-1,0
  4745.7    0.07       0  4983.3    0.07       0  4995.9    0.07       0
Bank Sta=4983.3,4995.9
Exp/Cntr=0.3,0.1

Type RM Length L Ch R = 1,2574,499,499,499
BEGIN DESCRIPTION:
Sweetwater Creek Trib 21 4.0
END DESCRIPTION:
XS GIS Cut Line= 3
      1385155.02      6847687.97      1385221.28      6847605.23
      1385505.01      6846787.98
#Sta/Elev= 30
  4894.0 2112.66  4901.2 2112.64  4921.7 2110.01  4936.4 2106.51  4944.4 2103.16
  4950.8 2103.75  4965.2 2097.63  4977.0 2095.89  5007.7 2093.11  5018.8 2090.36
  5019.3 2089.86  5031.4 2090.36  5039.4 2092.70  5050.0 2094.06  5081.7 2096.12
  5092.6 2098.00  5175.4 2098.06  5251.1 2101.43  5325.2 2103.38  5450.2 2103.17
  5455.5 2102.30  5481.3 2103.61  5486.6 2102.93  5668.1 2104.25  5725.0 2105.72
  5730.3 2107.27  5738.1 2106.41  5756.1 2107.00  5792.6 2110.63  5865.1 2113.85
#Mann=5,-1,0
  4894.0    0.07       0  4921.7    0.16       0  4977.0    0.07       0
  5018.8    0.07       0  5031.4    0.07       0
Bank Sta=5018.8,5031.4
Exp/Cntr=0.3,0.1

Type RM Length L Ch R = 1,2075,634,634,634
BEGIN DESCRIPTION:
Sweetwater Creek Trib 21 3.0
END DESCRIPTION:
XS GIS Cut Line= 3
      1385604.99      6847637.95      1385534.58      6847357.76
      1385704.99      6846888.02
#Sta/Elev= 30
  4711.1 2115.95  4742.0 2113.82  4770.2 2108.95  4834.8 2102.77  4863.9 2097.91
  4879.5 2095.83  4917.3 2093.48  4989.4 2091.80  4990.9 2086.16  4991.4 2085.66
  5003.7 2086.16  5015.8 2092.36  5021.1 2089.32  5031.7 2088.83  5046.4 2090.21
  5052.9 2092.30  5063.6 2091.03  5077.0 2091.31  5102.3 2095.63  5107.7 2094.58
  5127.4 2097.77  5133.0 2099.93  5138.3 2099.33  5148.7 2100.92  5201.9 2101.26
  5255.4 2095.99  5265.7 2096.30  5329.5 2102.44  5397.9 2104.92  5499.7 2112.49
#Mann=5,-1,0
  4711.1    0.07       0  4863.9    0.16       0  4879.5    0.07       0
  4990.9    0.07       0  5003.7    0.07       0
Bank Sta=4990.9,5003.7
Exp/Cntr=0.3,0.1

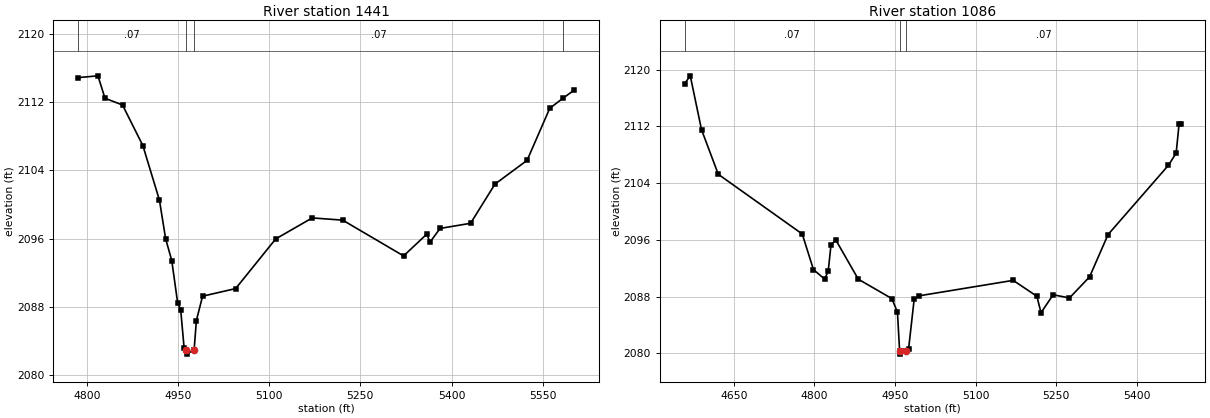
Type RM Length L Ch R = 1,1441,355,355,355
BEGIN DESCRIPTION:
Sweetwater Creek Trib 21 2.0
END DESCRIPTION:
XS GIS Cut Line= 3
      1385883.61      6847700.02      1385917.24      6847488.48
      1385955.00      6846887.97
#Sta/Elev= 30
  4785.8 2114.86  4818.2 2115.07  4829.9 2112.44  4858.7 2111.65  4892.2 2106.89
  4919.5 2100.48  4929.6 2095.98  4939.7 2093.43  4949.3 2088.50  4954.4 2087.64
  4960.0 2083.21  4963.7 2082.96  4964.2 2082.46  4976.5 2082.96  4980.2 2086.40
  4990.4 2089.25  5044.8 2090.14  5110.7 2095.96  5170.8 2098.42  5220.9 2098.16
  5321.1 2093.97  5359.4 2096.53  5364.4 2095.57  5381.2 2097.19  5431.3 2097.79
  5471.4 2102.38  5524.3 2105.17  5561.6 2111.27  5582.9 2112.42  5601.7 2113.40
#Mann=4,-1,0
  4785.8    0.07       0  4963.7    0.07       0  4976.5    0.07       0
  5582.9   0.035       0
Bank Sta=4963.7,4976.5
Exp/Cntr=0.3,0.1

Type RM Length L Ch R = 1,1086,0,0,0
BEGIN DESCRIPTION:
Sweetwater Creek Trib 21 1.0
END DESCRIPTION:
XS GIS Cut Line= 3
      1386104.99      6847788.02      1386228.34      6847364.41
      1386004.98      6846937.96
#Sta/Elev= 30
  4558.8 2118.04  4569.2 2119.13  4590.1 2111.54  4621.3 2105.25  4777.5 2096.83
  4798.4 2091.80  4819.2 2090.47  4825.8 2091.59  4831.0 2095.29  4840.0 2095.98
  4881.7 2090.46  4944.2 2087.72  4954.6 2085.82  4958.6 2080.39  4959.1 2079.89
  4971.4 2080.39  4975.4 2080.66  4985.8 2087.68  4995.5 2088.12  5169.9 2090.29
  5214.0 2088.05  5221.7 2085.73  5244.3 2088.26  5274.6 2087.81  5312.0 2090.78
  5346.4 2096.75  5458.8 2106.52  5473.1 2108.24  5478.5 2112.31  5481.4 2112.31
#Mann=3,-1,0
  4558.8    0.07       0  4958.6    0.07       0  4971.4    0.07       0
Bank Sta=4958.6,4971.4
Exp/Cntr=0.3,0.1

Chan Stop Cuts=-1