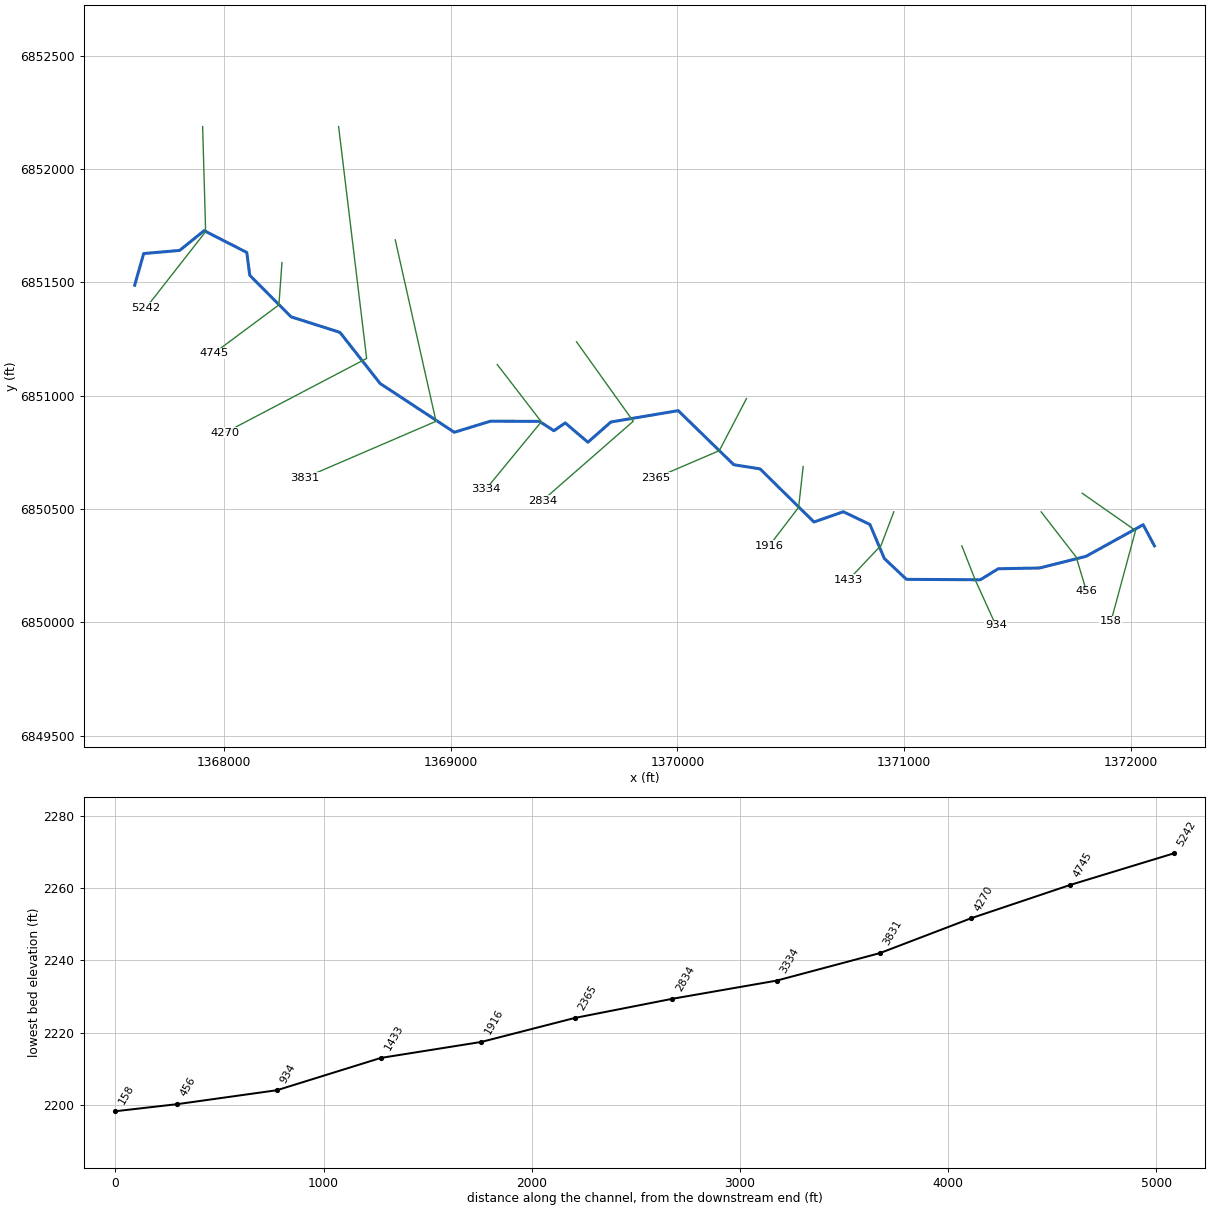
--- Sweetwater Creek Trib 21 T1.prj (project) ---

Proj Title=Sweetwater Creek Trib 21 T1 Base Level Engineering
Current Plan=p01
Default Exp/Contr=0.3,0.1
English Units
Geom File=g01
Flow File=f01
Plan File=p01
BEGIN DESCRIPTION:
Sweetwater Creek Trib 21 T1
END DESCRIPTION:

--- Sweetwater Creek Trib 21 T1.p01 (plan) ---

Plan Title=Multiple Run
Short Identifier=Multiple
Geom File=g01
Flow File=f01
Subcritical Flow
K Sum by GR= 0
Std Step Tol= 0.01
Critical Tol= 0.01
Num of Std Step Trials= 20
Max Error Tol= 0.3
Flow Tol Ratio= 0.001
Split Flow NTrial= 30
Split Flow Tol= 0.02
Split Flow Ratio= 0.02
Log Output Level= 0
Friction Slope Method= 1
Unsteady Friction Slope Method= 2
Unsteady Bridges Friction Slope Method= 1
Parabolic Critical Depth
Global Vel Dist=  1 , 1 , 1
Global Log Level= 0
CheckData=True
Encroach Param= -1, 0, 0, 0
BEGIN DESCRIPTION:
Multiple Run
END DESCRIPTION:

--- Sweetwater Creek Trib 21 T1.f01 (steady flow) ---

Flow Title=Multiple
Number of Profiles=7
Profile Names=10-year,25-year,50-year,1pct_min,100-year,1pct_plu,500-year
River Rch & RM= Sweetwater Creek,Reach-1,5242
     138     190     233     142     284     566     426
Boundary for River Rch & Prof#=Sweetwater Creek,Reach-1,1
Up Type=0
Dn Type=3
Dn Slope=0.005
Boundary for River Rch & Prof#=Sweetwater Creek,Reach-1,2
Up Type=0
Dn Type=3
Dn Slope=0.005
Boundary for River Rch & Prof#=Sweetwater Creek,Reach-1,3
Up Type=0
Dn Type=3
Dn Slope=0.005
Boundary for River Rch & Prof#=Sweetwater Creek,Reach-1,4
Up Type=0
Dn Type=3
Dn Slope=0.005
Boundary for River Rch & Prof#=Sweetwater Creek,Reach-1,5
Up Type=0
Dn Type=3
Dn Slope=0.005
Boundary for River Rch & Prof#=Sweetwater Creek,Reach-1,6
Up Type=0
Dn Type=3
Dn Slope=0.005
Boundary for River Rch & Prof#=Sweetwater Creek,Reach-1,7
Up Type=0
Dn Type=3
Dn Slope=0.005

--- Sweetwater Creek Trib 21 T1.g01 (geometry) ---

Geom Title=Existing Conditions

River Reach=Sweetwater Creek,Reach-1
Reach XY= 30
      1367605.00      6851488.00      1367644.83      6851627.70
      1367803.53      6851641.57      1367911.55      6851728.75
      1368099.75      6851632.56      1368112.88      6851531.88
      1368295.21      6851348.52      1368511.06      6851279.86
      1368687.95      6851054.50      1369015.54      6850839.08
      1369175.03      6850887.93      1369391.14      6850887.18
      1369455.10      6850845.81      1369505.01      6850880.43
      1369604.99      6850795.11      1369706.47      6850884.43
      1370003.50      6850934.54      1370248.83      6850695.86
      1370364.79      6850677.48      1370602.70      6850443.09
      1370732.21      6850488.38      1370849.42      6850432.42
      1370913.13      6850281.93      1371010.84      6850190.05
      1371336.73      6850188.21      1371415.51      6850236.78
      1371599.06      6850240.26      1371803.44      6850291.76
      1372055.26      6850430.95      1372105.00      6850338.00

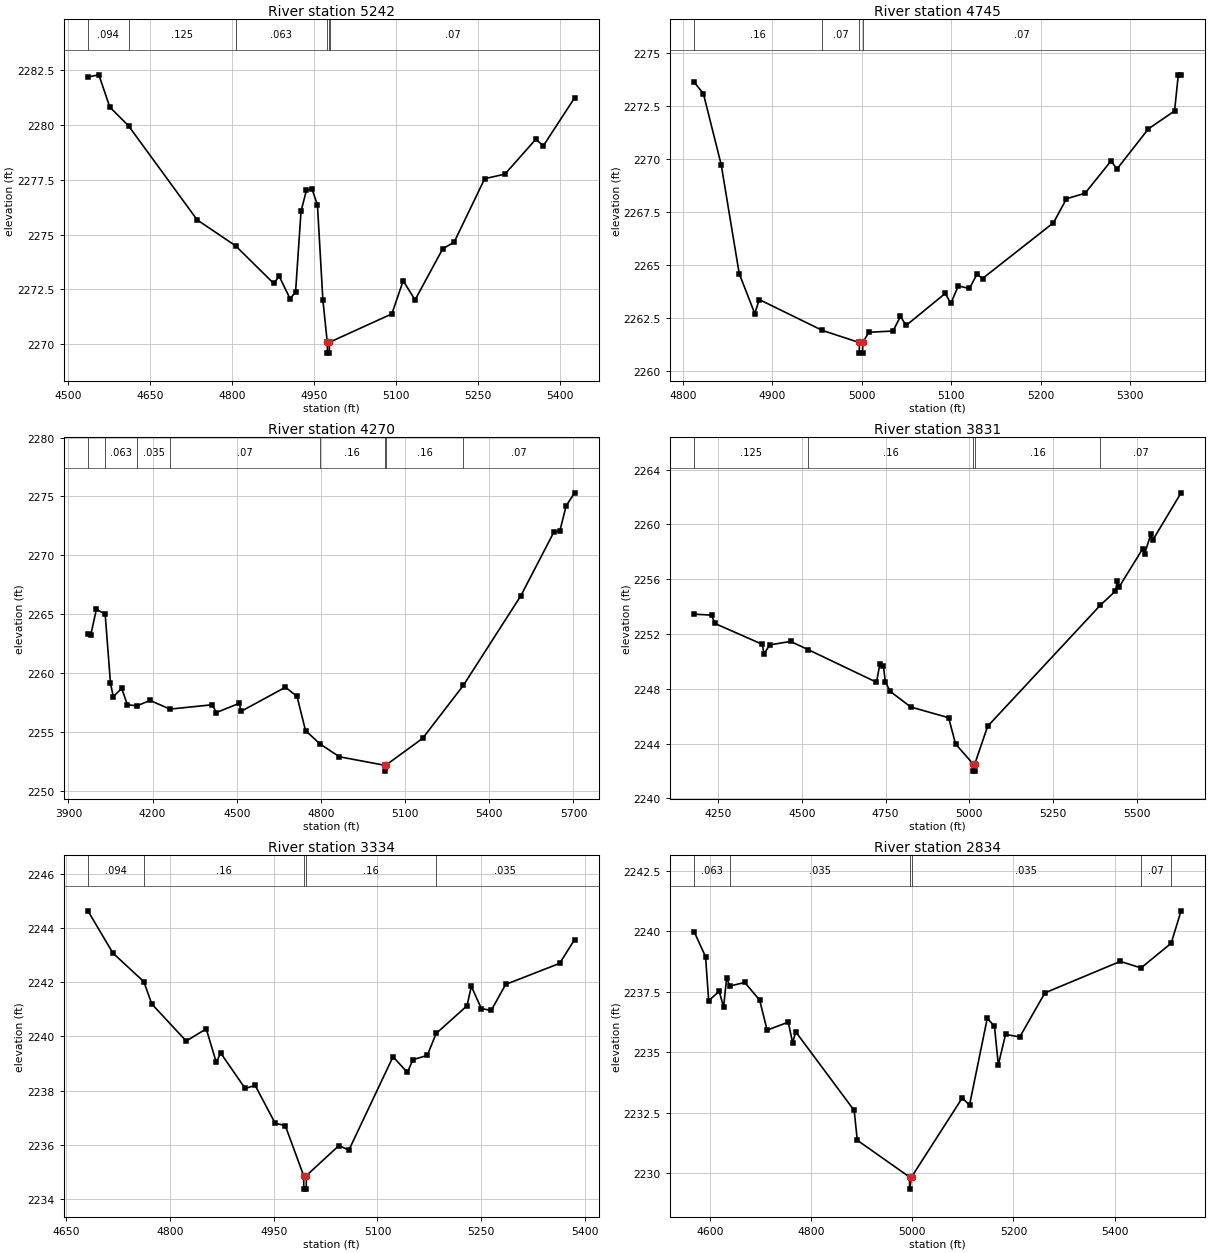
Type RM Length L Ch R = 1,5242,497,497,497
BEGIN DESCRIPTION:
Sweetwater Creek Trib 21 T1 10.0
END DESCRIPTION:
XS GIS Cut Line= 3
      1367905.00      6852188.05      1367918.19      6851724.24
      1367655.00      6851387.99
#Sta/Elev= 30
  4536.0 2282.19  4556.1 2282.29  4576.1 2280.82  4610.5 2279.96  4736.1 2275.67
  4806.3 2274.49  4876.2 2272.77  4886.2 2273.10  4906.2 2272.07  4916.2 2272.38
  4926.2 2276.07  4936.2 2277.03  4946.2 2277.08  4956.2 2276.36  4966.2 2272.01
  4974.2 2270.09  4974.5 2269.59  4978.0 2269.59  4978.2 2270.09  4979.5 2270.10
  5092.4 2271.38  5113.2 2272.89  5134.9 2272.02  5185.6 2274.35  5206.4 2274.65
  5262.4 2277.55  5299.5 2277.76  5355.6 2279.34  5370.0 2279.06  5427.0 2281.24
#Mann=6,-1,0
  4536.0   0.094       0  4610.5   0.125       0  4806.3   0.063       0
  4974.2    0.07       0  4978.2   0.063       0  4979.5    0.07       0
Bank Sta=4974.2,4978.2
Exp/Cntr=0.3,0.1

Type RM Length L Ch R = 1,4745,475,475,475
BEGIN DESCRIPTION:
Sweetwater Creek Trib 21 T1 9.0
END DESCRIPTION:
XS GIS Cut Line= 3
      1368255.00      6851588.03      1368241.62      6851401.21
      1367955.02      6851188.01
#Sta/Elev= 30
  4812.7 2273.59  4822.8 2273.07  4842.8 2269.71  4862.9 2264.60  4880.3 2262.72
  4885.3 2263.38  4955.8 2261.93  4997.1 2261.36  4997.4 2260.86  5000.9 2260.86
  5001.1 2261.36  5007.9 2261.84  5035.0 2261.90  5043.3 2262.59  5049.6 2262.16
  5093.4 2263.67  5099.6 2263.20  5108.0 2264.02  5120.5 2263.90  5128.8 2264.57
  5135.1 2264.37  5214.4 2266.99  5229.0 2268.12  5249.8 2268.38  5279.0 2269.91
  5285.3 2269.51  5320.7 2271.41  5349.9 2272.25  5354.1 2273.95  5357.2 2273.95
#Mann=4,-1,0
  4812.7    0.16       0  4955.8    0.07       0  4997.1    0.07       0
  5001.1    0.07       0
Bank Sta=4997.1,5001.1
Exp/Cntr=0.3,0.1

Type RM Length L Ch R = 1,4270,439,439,439
BEGIN DESCRIPTION:
Sweetwater Creek Trib 21 T1 8.0
END DESCRIPTION:
XS GIS Cut Line= 3
      1368505.00      6852187.97      1368628.70      6851164.82
      1368005.04      6850838.02
#Sta/Elev= 30
  3969.4 2263.32  3979.4 2263.20  3999.6 2265.40  4031.0 2265.01  4049.9 2259.14
  4060.0 2257.98  4089.8 2258.70  4110.4 2257.29  4145.6 2257.22  4191.0 2257.67
  4261.9 2256.93  4412.6 2257.30  4427.6 2256.64  4509.6 2257.43  4514.6 2256.73
  4673.5 2258.79  4714.8 2258.01  4745.0 2255.11  4796.7 2253.97  4865.8 2252.88
  5026.9 2252.16  5027.2 2251.66  5030.9 2252.16  5162.2 2254.44  5307.4 2258.94
  5512.2 2266.55  5629.7 2271.95  5651.8 2272.10  5673.9 2274.20  5704.1 2275.31
#Mann=8,-1,0
  3969.4   0.094       0  4031.0   0.063       0  4145.6   0.035       0
  4261.9    0.07       0  4796.7    0.16       0  5026.9    0.07       0
  5030.9    0.16       0  5307.4    0.07       0
Bank Sta=5026.9,5030.9
Exp/Cntr=0.3,0.1

Type RM Length L Ch R = 1,3831,497,497,497
BEGIN DESCRIPTION:
Sweetwater Creek Trib 21 T1 7.0
END DESCRIPTION:
XS GIS Cut Line= 3
      1368755.01      6851687.95      1368934.79      6850887.49
      1368354.99      6850638.00
#Sta/Elev= 30
  4179.6 2253.45  4230.8 2253.38  4241.0 2252.77  4382.2 2251.25  4387.3 2250.56
  4405.0 2251.21  4466.5 2251.46  4520.0 2250.85  4722.8 2248.48  4733.0 2249.82
  4743.3 2249.69  4749.2 2248.50  4763.8 2247.81  4825.2 2246.67  4938.0 2245.89
  4958.5 2243.98  5011.7 2242.49  5012.0 2241.99  5015.5 2241.99  5015.7 2242.49
  5054.2 2245.26  5390.6 2254.11  5435.2 2255.13  5441.1 2255.87  5446.5 2255.44
  5517.1 2258.24  5522.6 2257.86  5540.7 2259.27  5546.1 2258.83  5631.2 2262.31
#Mann=5,-1,0
  4179.6   0.125       0  4520.0    0.16       0  5011.7    0.07       0
  5015.7    0.16       0  5390.6    0.07       0
Bank Sta=5011.7,5015.7
Exp/Cntr=0.3,0.1

Type RM Length L Ch R = 1,3334,500,500,500
BEGIN DESCRIPTION:
Sweetwater Creek Trib 21 T1 6.0
END DESCRIPTION:
XS GIS Cut Line= 3
      1369205.01      6851137.99      1369399.56      6850885.43
      1369154.98      6850587.97
#Sta/Elev= 30
  4681.2 2244.64  4717.4 2243.08  4762.2 2242.02  4773.6 2241.20  4823.4 2239.83
  4852.4 2240.28  4866.9 2239.04  4873.2 2239.39  4908.6 2238.08  4923.1 2238.19
  4952.1 2236.79  4966.6 2236.71  4993.2 2234.86  4993.5 2234.36  4997.0 2234.36
  4997.2 2234.86  5044.3 2235.97  5058.6 2235.80  5122.5 2239.25  5143.3 2238.67
  5151.2 2239.14  5172.0 2239.30  5184.9 2240.11  5229.4 2241.13  5235.8 2241.85
  5250.2 2241.03  5264.5 2240.96  5285.3 2241.92  5363.5 2242.70  5385.1 2243.58
#Mann=5,-1,0
  4681.2   0.094       0  4762.2    0.16       0  4993.2    0.07       0
  4997.2    0.16       0  5184.9   0.035       0
Bank Sta=4993.2,4997.2
Exp/Cntr=0.3,0.1

Type RM Length L Ch R = 1,2834,469,469,469
BEGIN DESCRIPTION:
Sweetwater Creek Trib 21 T1 5.0
END DESCRIPTION:
XS GIS Cut Line= 3
      1369554.98      6851238.03      1369805.14      6850887.67
      1369404.99      6850538.00
#Sta/Elev= 30
  4569.5 2239.96  4591.7 2238.94  4597.8 2237.13  4618.7 2237.51  4627.3 2236.86
  4633.4 2238.08  4639.3 2237.73  4669.1 2237.88  4698.6 2237.15  4713.3 2235.91
  4755.1 2236.24  4763.7 2235.39  4769.9 2235.84  4885.4 2232.59  4891.5 2231.36
  4994.7 2229.84  4995.0 2229.34  4998.7 2229.84  5099.0 2233.11  5113.3 2232.81
  5148.4 2236.40  5162.6 2236.07  5170.2 2234.48  5184.5 2235.73  5212.7 2235.63
  5262.3 2237.45  5411.3 2238.75  5452.3 2238.48  5511.8 2239.50  5531.4 2240.84
#Mann=6,-1,0
  4569.5   0.063       0  4639.3   0.035       0  4994.7   0.035       0
  4998.7   0.035       0  5452.3    0.07       0  5511.8   0.035       0
Bank Sta=4994.7,4998.7
Exp/Cntr=0.3,0.1

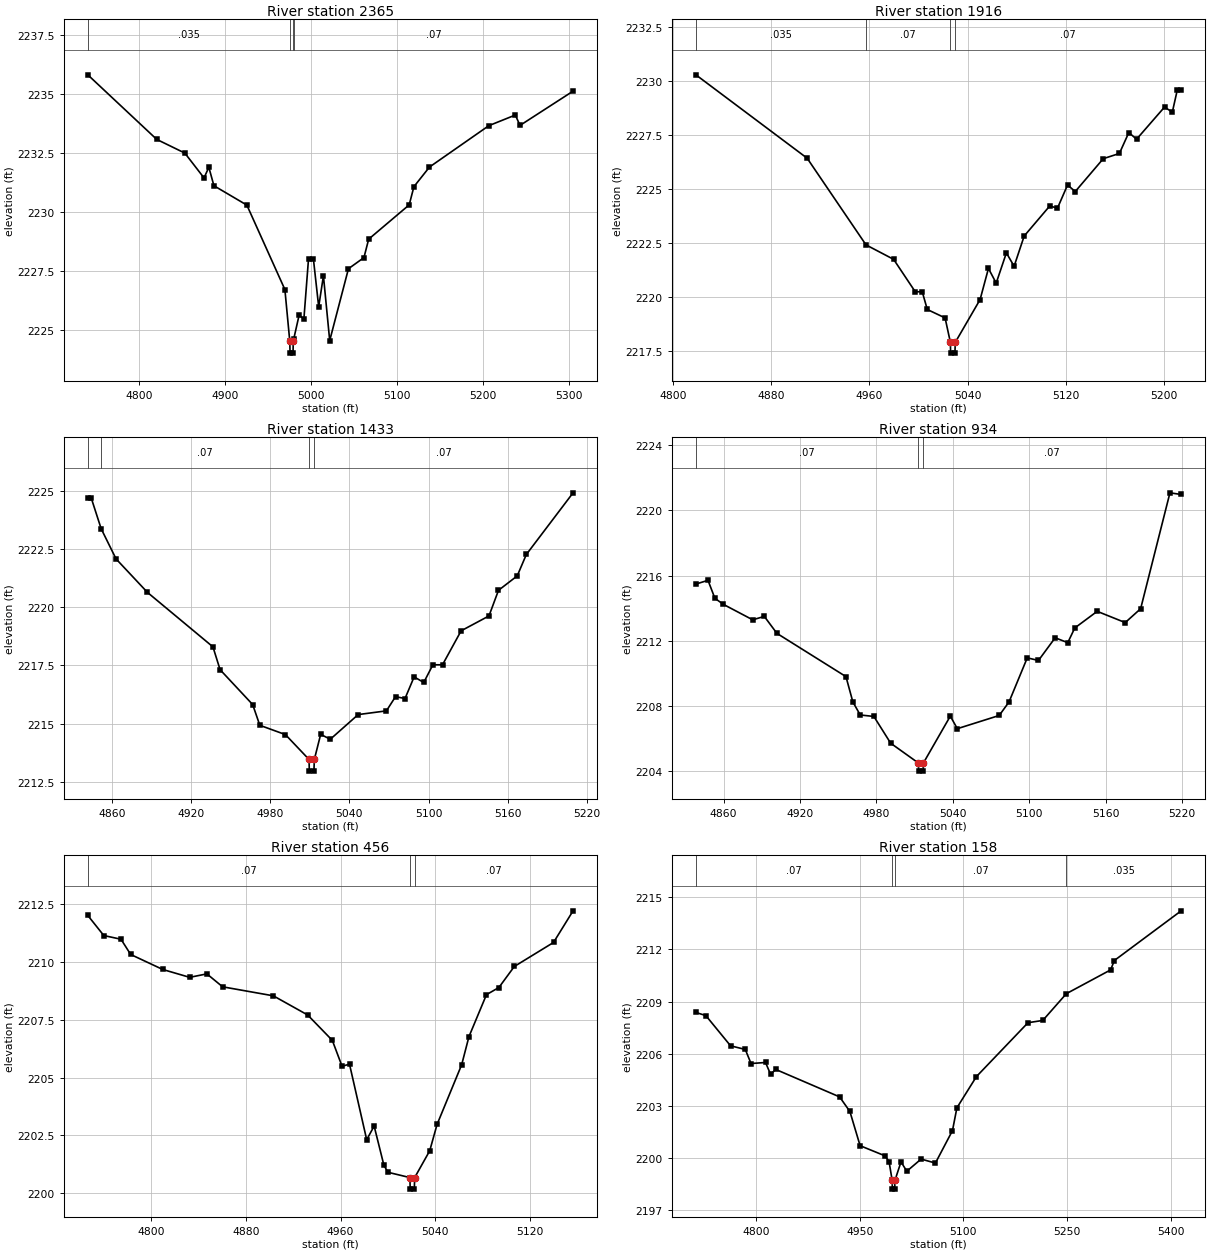
Type RM Length L Ch R = 1,2365,449,449,449
BEGIN DESCRIPTION:
Sweetwater Creek Trib 21 T1 4.0
END DESCRIPTION:
XS GIS Cut Line= 3
      1370305.00      6850987.99      1370184.97      6850757.92
      1369904.97      6850637.99
#Sta/Elev= 30
  4740.5 2235.80  4820.6 2233.07  4853.3 2232.49  4875.6 2231.44  4881.2 2231.89
  4887.1 2231.11  4925.4 2230.29  4969.6 2226.72  4975.3 2224.53  4975.6 2224.03
  4979.1 2224.03  4979.3 2224.53  4979.9 2224.63  4986.1 2225.63  4991.7 2225.48
  4997.1 2228.03  5002.7 2228.03  5008.9 2225.99  5014.4 2227.30  5021.7 2224.56
  5043.5 2227.60  5061.5 2228.07  5067.0 2228.85  5114.1 2230.30  5119.6 2231.07
  5137.7 2231.90  5206.7 2233.65  5237.5 2234.10  5242.9 2233.66  5304.6 2235.11
#Mann=4,-1,0
  4740.5   0.035       0  4975.3    0.07       0  4979.3   0.035       0
  4979.9    0.07       0
Bank Sta=4975.3,4979.3
Exp/Cntr=0.3,0.1

Type RM Length L Ch R = 1,1916,483,483,483
BEGIN DESCRIPTION:
Sweetwater Creek Trib 21 T1 3.0
END DESCRIPTION:
XS GIS Cut Line= 3
      1370555.00      6850688.00      1370534.97      6850507.91
      1370405.01      6850338.01
#Sta/Elev= 30
  4818.8 2230.27  4909.4 2226.41  4957.3 2222.40  4979.8 2221.73  4997.4 2220.23
  5003.1 2220.23  5007.2 2219.41  5021.7 2219.02  5026.0 2217.89  5026.2 2217.39
  5029.7 2217.39  5030.0 2217.89  5050.2 2219.87  5057.0 2221.31  5063.3 2220.63
  5071.6 2222.03  5077.9 2221.41  5086.1 2222.81  5106.9 2224.20  5113.2 2224.10
  5121.4 2225.17  5127.7 2224.87  5150.5 2226.39  5163.6 2226.63  5171.3 2227.60
  5177.6 2227.29  5200.4 2228.78  5206.7 2228.54  5210.8 2229.58  5213.9 2229.58
#Mann=4,-1,0
  4818.8   0.035       0  4957.3    0.07       0  5026.0    0.07       0
  5030.0    0.07       0
Bank Sta=5026,5030
Exp/Cntr=0.3,0.1

Type RM Length L Ch R = 1,1433,499,499,499
BEGIN DESCRIPTION:
Sweetwater Creek Trib 21 T1 2.0
END DESCRIPTION:
XS GIS Cut Line= 3
      1370955.01      6850488.03      1370898.91      6850340.22
      1370754.99      6850187.99
#Sta/Elev= 30
  4841.9 2224.68  4844.6 2224.68  4852.0 2223.38  4863.3 2222.08  4887.1 2220.64
  4936.7 2218.30  4942.1 2217.32  4966.8 2215.82  4972.2 2214.93  4991.6 2214.53
  5009.5 2213.46  5009.7 2212.96  5013.2 2212.96  5013.5 2213.46  5018.3 2214.54
  5025.6 2214.33  5046.7 2215.39  5068.1 2215.55  5075.0 2216.16  5082.2 2216.08
  5089.1 2217.01  5096.4 2216.77  5103.3 2217.53  5110.6 2217.53  5124.7 2218.99
  5145.8 2219.63  5153.0 2220.73  5167.2 2221.35  5174.1 2222.27  5209.5 2224.92
#Mann=4,-1,0
  4841.9   0.035       0  4852.0    0.07       0  5009.5    0.07       0
  5013.5    0.07       0
Bank Sta=5009.5,5013.5
Exp/Cntr=0.3,0.1

Type RM Length L Ch R = 1,934,478,478,478
BEGIN DESCRIPTION:
Sweetwater Creek Trib 21 T1 1.0
END DESCRIPTION:
XS GIS Cut Line= 3
      1371255.00      6850337.99      1371314.28      6850187.55
      1371405.00      6849988.00
#Sta/Elev= 30
  4838.3 2215.48  4847.8 2215.71  4853.2 2214.61  4859.8 2214.24  4882.9 2213.29
  4892.0 2213.50  4901.9 2212.46  4956.1 2209.81  4961.5 2208.26  4967.3 2207.46
  4978.0 2207.37  4991.2 2205.73  5012.9 2204.52  5013.2 2204.02  5016.7 2204.02
  5016.9 2204.52  5038.0 2207.39  5043.5 2206.62  5076.4 2207.43  5084.1 2208.26
  5098.4 2210.96  5107.2 2210.80  5120.3 2212.19  5130.2 2211.89  5135.7 2212.79
  5153.3 2213.81  5175.3 2213.12  5187.4 2213.97  5210.4 2221.07  5219.2 2220.97
#Mann=3,-1,0
  4838.3    0.07       0  5012.9    0.07       0  5016.9    0.07       0
Bank Sta=5012.9,5016.9
Exp/Cntr=0.3,0.1

Type RM Length L Ch R = 1,456,298,298,298
BEGIN DESCRIPTION:
Sweetwater Creek Trib 21 T1 2744
END DESCRIPTION:
XS GIS Cut Line= 3
      1371605.02      6850487.98      1371760.16      6850287.62
      1371805.00      6850137.99
#Sta/Elev= 30
  4746.6 2212.02  4760.1 2211.15  4774.6 2210.99  4782.8 2210.33  4809.9 2209.68
  4832.6 2209.34  4847.1 2209.49  4860.4 2208.93  4903.2 2208.54  4932.2 2207.71
  4953.0 2206.61  4961.2 2205.49  4967.5 2205.58  4982.0 2202.31  4988.3 2202.90
  4996.5 2201.21  4999.9 2200.90  5018.5 2200.67  5018.7 2200.17  5022.2 2200.17
  5022.5 2200.67  5035.2 2201.83  5041.4 2202.97  5062.2 2205.56  5068.3 2206.77
  5083.1 2208.59  5093.6 2208.90  5106.6 2209.81  5139.7 2210.85  5156.2 2212.22
#Mann=3,-1,0
  4746.6    0.07       0  5018.5    0.07       0  5022.5    0.07       0
Bank Sta=5018.5,5022.5
Exp/Cntr=0.3,0.1

Type RM Length L Ch R = 1,158,0,0,0
BEGIN DESCRIPTION:
Sweetwater Creek Trib 21 T1 4484
END DESCRIPTION:
XS GIS Cut Line= 3
      1371786.37      6850569.99      1372021.71      6850405.55
      1371913.29      6850004.65
#Sta/Elev= 30
  4712.9 2208.37  4727.3 2208.19  4763.1 2206.45  4784.4 2206.24  4792.7 2205.43
  4813.7 2205.49  4821.0 2204.81  4828.5 2205.09  4920.9 2203.51  4935.8 2202.67
  4950.6 2200.70  4986.4 2200.12  4992.5 2199.79  4997.0 2198.70  4997.2 2198.20
  5000.7 2198.20  5001.0 2198.70  5009.8 2199.77  5018.2 2199.23  5038.9 2199.93
  5059.6 2199.70  5084.3 2201.57  5090.7 2202.88  5119.0 2204.68  5193.6 2207.78
  5215.0 2207.91  5249.1 2209.45  5313.2 2210.82  5318.6 2211.36  5415.3 2214.22
#Mann=4,-1,0
  4712.9    0.07       0  4997.0    0.07       0  5001.0    0.07       0
  5249.1   0.035       0
Bank Sta=4997,5001
Exp/Cntr=0.3,0.1

Chan Stop Cuts=-1