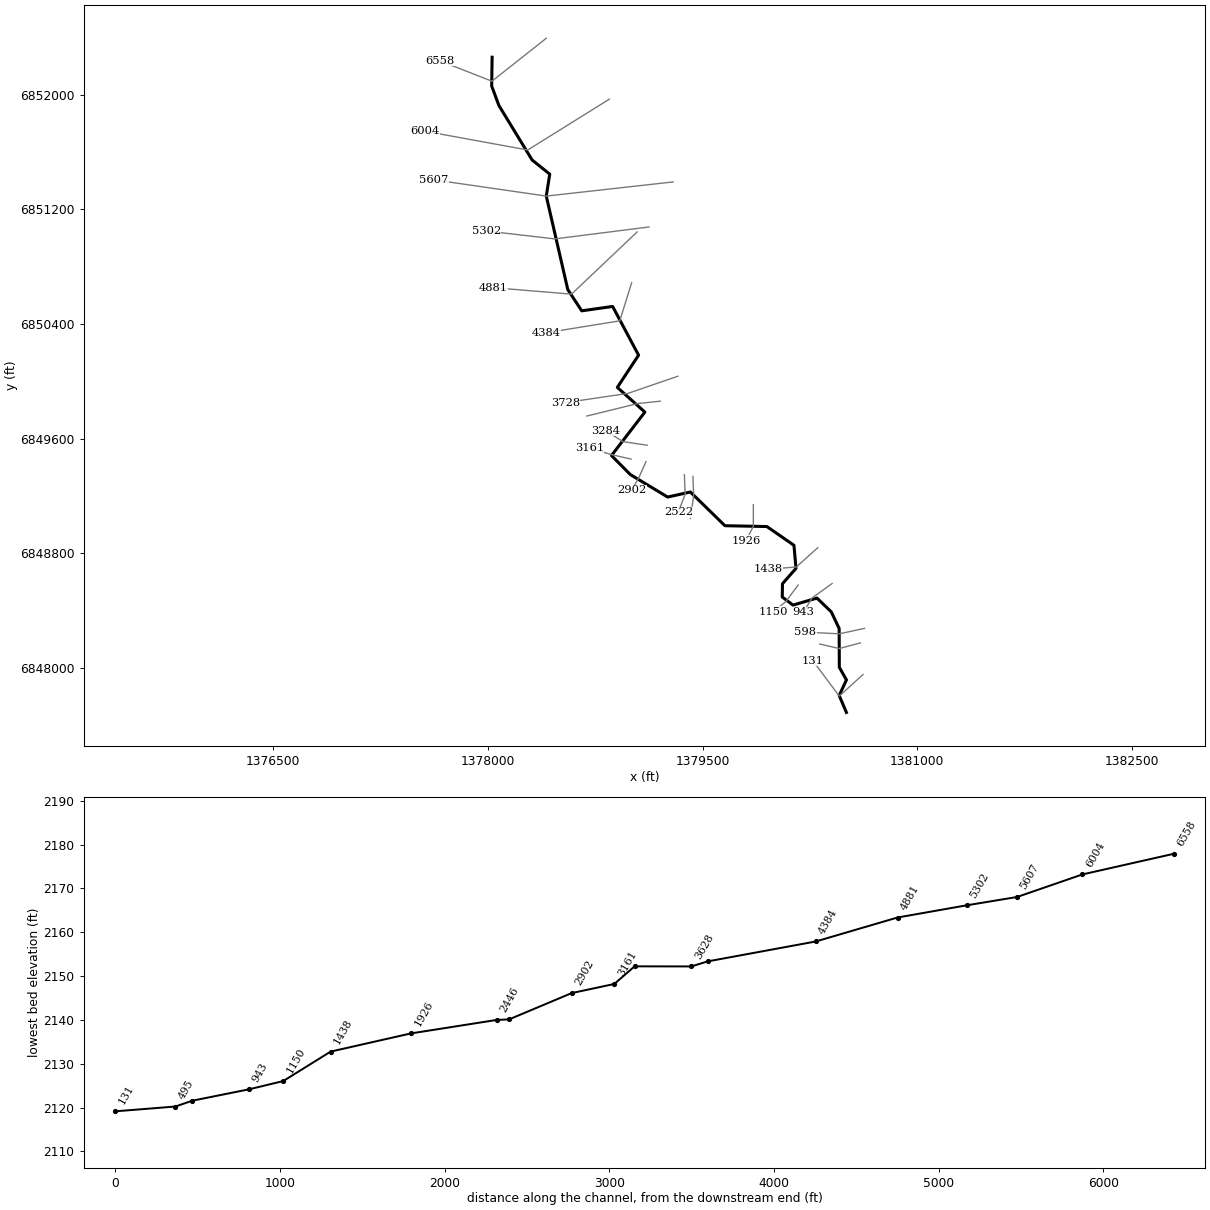
--- Sweetwater Creek Trib 21 T2.prj (project) ---

Proj Title=Sweetwater Creek Trib 21 T2 Base Level Engineering
Current Plan=p01
Default Exp/Contr=0.3,0.1
English Units
Geom File=g01
Flow File=f01
Plan File=p01
Y Axis Title=Elevation
X Axis Title(PF)=Main Channel Distance
X Axis Title(XS)=Station
BEGIN DESCRIPTION:
Sweetwater Creek Trib 21 T2
END DESCRIPTION:
DSS Export Rating Curves= 0
DSS Export Rating Curve Sorted= 0
DSS Export Volume Flow Curves= 0
DXF OffsetX= 0
DXF OffsetY= 0
DXF ScaleX= 1
DXF ScaleY= 10

--- Sweetwater Creek Trib 21 T2.p01 (plan) ---

Plan Title=Multiple Run
Short Identifier=Multiple
Geom File=g01
Flow File=f01
Subcritical Flow
K Sum by GR= 0
Std Step Tol= 0.01
Critical Tol= 0.01
Num of Std Step Trials= 20
Max Error Tol= 0.3
Flow Tol Ratio= 0.001
Split Flow NTrial= 30
Split Flow Tol= 0.02
Split Flow Ratio= 0.02
Log Output Level= 0
Friction Slope Method= 1
Unsteady Friction Slope Method= 2
Unsteady Bridges Friction Slope Method= 1
Parabolic Critical Depth
Global Vel Dist=  1 , 1 , 1
Global Log Level= 0
CheckData=True
Encroach Param= -1, 0, 0, 0
BEGIN DESCRIPTION:
Multiple Run
END DESCRIPTION:

--- Sweetwater Creek Trib 21 T2.f01 (steady flow) ---

Flow Title=Multiple
Program Version=4.10
Number of Profiles= 7
Profile Names=10-year,25-year,50-year,1pct_min,100-year,1pct_plu,500-year
River Rch & RM=Sweetwater Creek,Reach-1         ,6558
     221     307     379     232     463     925     702
Boundary for River Rch & Prof#=Sweetwater Creek,Reach-1         , 1
Up Type= 0
Dn Type= 3
Dn Slope=0.005
Boundary for River Rch & Prof#=Sweetwater Creek,Reach-1         , 2
Up Type= 0
Dn Type= 3
Dn Slope=0.005
Boundary for River Rch & Prof#=Sweetwater Creek,Reach-1         , 3
Up Type= 0
Dn Type= 3
Dn Slope=0.005
Boundary for River Rch & Prof#=Sweetwater Creek,Reach-1         , 4
Up Type= 0
Dn Type= 3
Dn Slope=0.005
Boundary for River Rch & Prof#=Sweetwater Creek,Reach-1         , 5
Up Type= 0
Dn Type= 3
Dn Slope=0.005
Boundary for River Rch & Prof#=Sweetwater Creek,Reach-1         , 6
Up Type= 0
Dn Type= 3
Dn Slope=0.005
Boundary for River Rch & Prof#=Sweetwater Creek,Reach-1         , 7
Up Type= 0
Dn Type= 3
Dn Slope=0.005
DSS Import GetInterval= 0
DSS Import GetPeak= 0
DSS Import FillOption= 0

--- Sweetwater Creek Trib 21 T2.g01 (geometry) ---

Geom Title=Existing Conditions

River Reach=Sweetwater Creek,Reach-1
Reach XY= 30
      1378030.20      6852261.62      1378027.18      6852060.46
      1378077.56      6851924.48      1378309.77      6851544.06
      1378432.77      6851445.50      1378408.51      6851292.31
      1378558.82      6850639.58      1378656.28      6850491.37
      1378872.06      6850521.94      1379053.24      6850181.87
      1378904.77      6849956.76      1379097.41      6849784.67
      1378863.96      6849481.33      1378995.32      6849348.76
      1379256.50      6849191.47      1379415.05      6849226.88
      1379656.45      6848991.53      1379949.48      6848985.65
      1380138.59      6848854.80      1380152.94      6848693.86
      1380058.47      6848586.49      1380056.87      6848493.68
      1380132.12      6848437.38      1380299.38      6848486.27
      1380399.18      6848390.32      1380454.33      6848274.09
      1380455.54      6848003.21      1380505.37      6847915.19
      1380454.73      6847806.43      1380505.00      6847688.00

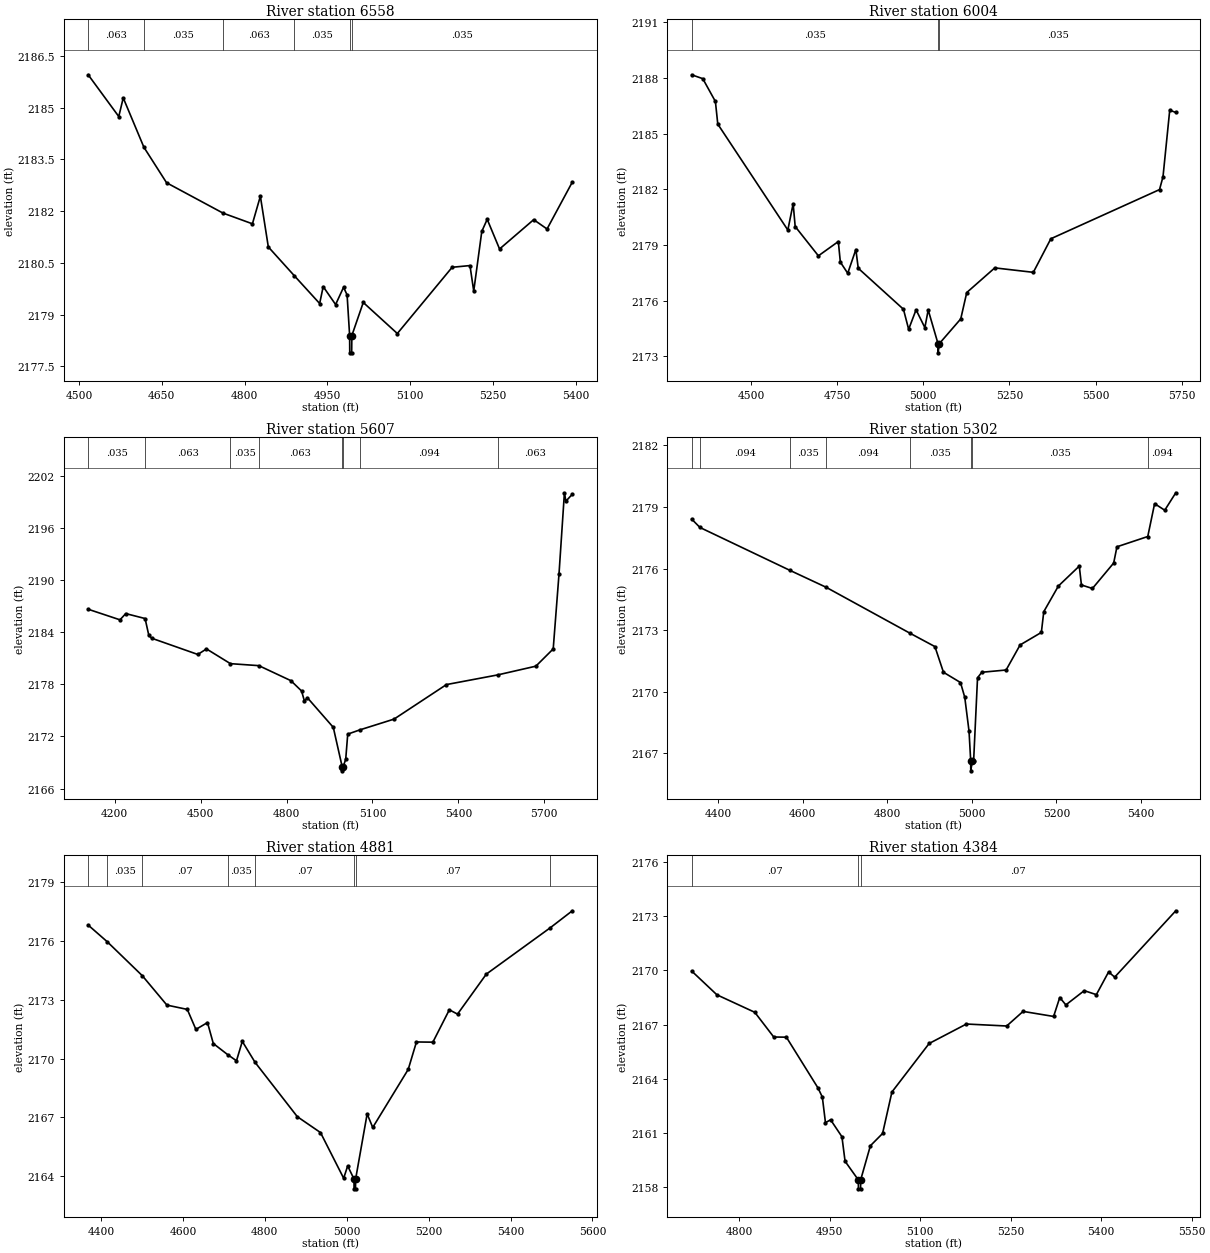
Type RM Length L Ch R = 1,6558,554,554,554
BEGIN DESCRIPTION:
Sweetwater Creek Trib 21 T2 13.0
END DESCRIPTION:
XS GIS Cut Line= 3
      1378408.13      6852393.67      1378029.03      6852094.07
      1377662.31      6852237.55
#Sta/Elev= 30
  4516.8 2185.95  4572.2 2184.74  4580.3 2185.28  4617.7 2183.85  4658.8 2182.82
  4761.1 2181.94  4814.3 2181.63  4828.7 2182.43  4843.1 2180.96  4890.5 2180.12
  4936.1 2179.32  4942.5 2179.81  4965.0 2179.29  4979.4 2179.79  4985.8 2179.57
  4990.4 2178.39  4990.6 2177.89  4994.1 2177.89  4994.4 2178.39  5015.1 2179.35
  5076.8 2178.45  5176.1 2180.37  5208.4 2180.42  5215.2 2179.68  5229.8 2181.41
  5239.6 2181.76  5262.0 2180.90  5323.8 2181.75  5348.0 2181.48  5393.8 2182.84
#Mann=6,-1,0
  4516.8   0.063       0  4617.7   0.035       0  4761.1   0.063       0
  4890.5   0.035       0  4990.4   0.035       0  4994.4   0.035       0
Bank Sta=4990.4,4994.4
Exp/Cntr=0.3,0.1

Type RM Length L Ch R = 1,6004,397,397,397
BEGIN DESCRIPTION:
Sweetwater Creek Trib 21 T2 12.0
END DESCRIPTION:
XS GIS Cut Line= 3
      1378849.40      6851968.86      1378278.92      6851613.89
      1377558.53      6851745.39
#Sta/Elev= 30
  4328.1 2188.18  4360.4 2187.97  4397.0 2186.74  4403.9 2185.52  4607.1 2179.81
  4622.5 2181.23  4628.4 2180.00  4695.7 2178.42  4753.5 2179.19  4759.4 2178.08
  4780.8 2177.48  4804.4 2178.76  4811.3 2177.75  4942.4 2175.54  4957.5 2174.46
  4979.0 2175.51  5004.5 2174.55  5014.2 2175.50  5042.6 2173.69  5042.9 2173.19
  5046.6 2173.69  5108.6 2175.02  5126.0 2176.44  5207.3 2177.77  5319.1 2177.53
  5369.9 2179.34  5685.1 2181.99  5695.2 2182.68  5714.7 2186.27  5732.3 2186.15
#Mann=3,-1,0
  4328.1   0.035       0  5042.6   0.035       0  5046.6   0.035       0
Bank Sta=5042.6,5046.6
Exp/Cntr=0.3,0.1

Type RM Length L Ch R = 1,5607,305,305,305
BEGIN DESCRIPTION:
Sweetwater Creek Trib 21 T2 11.0
END DESCRIPTION:
XS GIS Cut Line= 3
      1379295.32      6851391.15      1378408.51      6851292.31
      1377619.01      6851406.40
#Sta/Elev= 30
  4107.7 2186.66  4218.7 2185.44  4238.8 2186.16  4306.3 2185.59  4319.3 2183.66
  4329.4 2183.32  4490.4 2181.45  4520.6 2182.09  4604.2 2180.39  4703.5 2180.16
  4815.3 2178.43  4852.6 2177.24  4862.7 2176.06  4872.7 2176.47  4963.3 2173.05
  4994.1 2168.54  4994.4 2168.04  4998.1 2168.54  5006.7 2169.38  5013.7 2172.27
  5056.1 2172.76  5175.3 2174.00  5358.3 2177.98  5536.7 2179.09  5670.4 2180.10
  5731.0 2182.09  5751.2 2190.72  5770.1 2200.08  5775.2 2199.11  5797.7 2199.91
#Mann=8,-1,0
  4107.7   0.035       0  4306.3   0.063       0  4604.2   0.035       0
  4703.5   0.063       0  4994.1   0.063       0  4998.1   0.063       0
  5056.1   0.094       0  5536.7   0.063       0
Bank Sta=4994.1,4998.1
Exp/Cntr=0.3,0.1

Type RM Length L Ch R = 1,5302,421,421,421
BEGIN DESCRIPTION:
Sweetwater Creek Trib 21 T2 10.0
END DESCRIPTION:
XS GIS Cut Line= 3
      1379125.99      6851076.70      1378468.33      6850993.49
      1377989.09      6851048.60
#Sta/Elev= 30
  4337.1 2178.41  4356.8 2178.00  4569.8 2175.91  4655.1 2175.09  4852.8 2172.86
  4912.6 2172.20  4932.8 2170.95  4973.1 2170.45  4983.2 2169.73  4993.3 2168.08
  4997.2 2166.65  4997.4 2166.15  5001.2 2166.65  5004.2 2166.65  5013.4 2170.68
  5023.5 2170.95  5081.0 2171.06  5114.1 2172.28  5164.4 2172.89  5170.1 2173.90
  5204.7 2175.15  5254.1 2176.12  5259.2 2175.20  5285.2 2175.03  5335.5 2176.27
  5343.2 2177.06  5416.1 2177.56  5432.3 2179.16  5456.3 2178.84  5482.4 2179.69
#Mann=8,-1,0
  4337.1   0.063       0  4356.8   0.094       0  4569.8   0.035       0
  4655.1   0.094       0  4852.8   0.035       0  4997.2   0.035       0
  5001.2   0.035       0  5416.1   0.094       0
Bank Sta=4997.2,5001.2
Exp/Cntr=0.3,0.1

Type RM Length L Ch R = 1,4881,497,497,497
BEGIN DESCRIPTION:
Sweetwater Creek Trib 21 T2 9.0
END DESCRIPTION:
XS GIS Cut Line= 3
      1379043.09      6851041.83      1378584.72      6850607.88
      1378035.69      6850653.15
#Sta/Elev= 30
  4368.8 2176.81  4415.4 2175.96  4500.9 2174.23  4561.0 2172.73  4610.8 2172.51
  4631.8 2171.49  4660.1 2171.84  4674.3 2170.77  4709.0 2170.21  4730.9 2169.89
  4745.1 2170.88  4776.3 2169.81  4879.4 2167.04  4936.0 2166.23  4992.6 2163.90
  5002.4 2164.53  5017.8 2163.86  5018.0 2163.36  5021.5 2163.36  5021.8 2163.86
  5049.9 2167.18  5063.6 2166.49  5150.2 2169.45  5170.3 2170.85  5210.4 2170.84
  5250.6 2172.49  5270.6 2172.27  5340.9 2174.31  5496.8 2176.67  5550.9 2177.54
#Mann=8,-1,0
  4368.8    0.07       0  4415.4   0.035       0  4500.9    0.07       0
  4709.0   0.035       0  4776.3    0.07       0  5017.8    0.07       0
  5021.8    0.07       0  5496.8   0.035       0
Bank Sta=5017.8,5021.8
Exp/Cntr=0.3,0.1

Type RM Length L Ch R = 1,4384,656,656,656
BEGIN DESCRIPTION:
Sweetwater Creek Trib 21 T2 8.0
END DESCRIPTION:
XS GIS Cut Line= 3
      1379004.99      6850687.98      1378922.03      6850421.50
      1378405.03      6850338.01
#Sta/Elev= 30
  4720.9 2169.97  4762.8 2168.65  4825.6 2167.68  4857.0 2166.31  4878.0 2166.30
  4930.3 2163.49  4937.6 2162.98  4942.8 2161.56  4951.3 2161.72  4970.1 2160.78
  4975.3 2159.42  4997.2 2158.39  4997.5 2157.89  5001.0 2157.89  5001.2 2158.39
  5017.3 2160.28  5037.5 2160.96  5053.0 2163.26  5114.7 2165.95  5176.5 2167.03
  5243.3 2166.92  5270.5 2167.73  5321.1 2167.45  5331.3 2168.50  5341.4 2168.09
  5371.9 2168.88  5392.0 2168.66  5412.3 2169.92  5422.4 2169.63  5523.7 2173.31
#Mann=3,-1,0
  4720.9    0.07       0  4997.2    0.07       0  5001.2    0.07       0
Bank Sta=4997.2,5001.2
Exp/Cntr=0.3,0.1

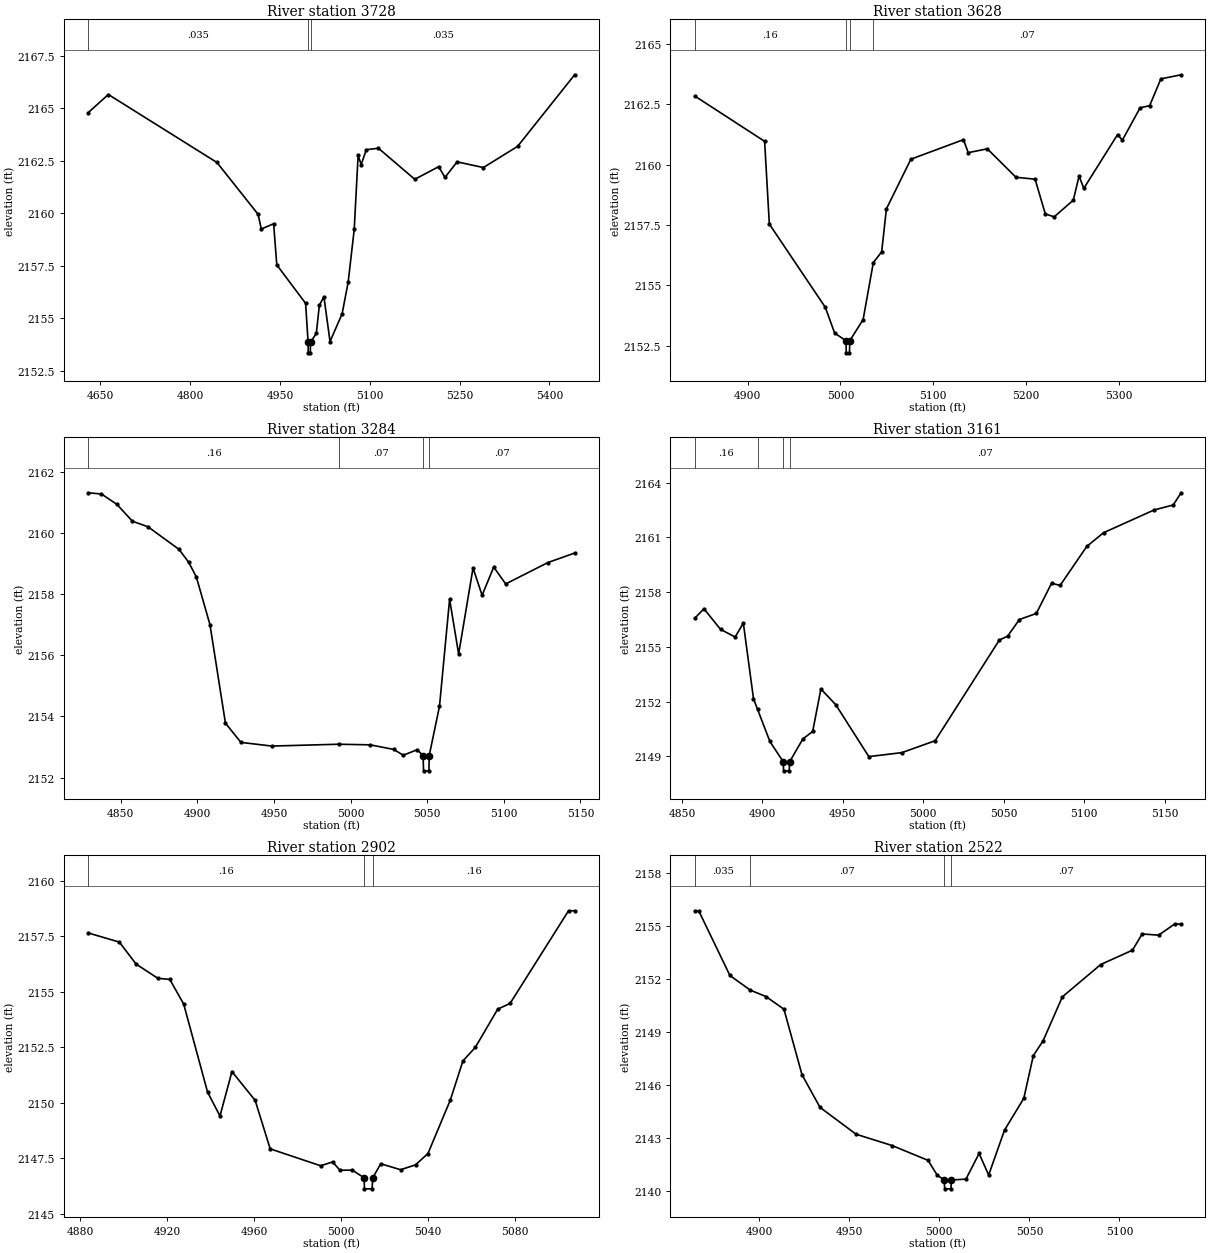
Type RM Length L Ch R = 1,3728,100,100,100
BEGIN DESCRIPTION:
Sweetwater Creek Trib 21 T2 7.0
END DESCRIPTION:
XS GIS Cut Line= 3
      1379328.26      6850035.04      1378978.29      6849914.93
      1378540.79      6849850.66
#Sta/Elev= 30
  4630.0 2164.80  4663.5 2165.66  4844.9 2162.42  4913.6 2159.95  4918.9 2159.25
  4939.5 2159.50  4944.8 2157.54  4992.9 2155.71  4997.1 2153.85  4997.3 2153.35
  5000.8 2153.35  5001.1 2153.85  5010.8 2154.28  5015.9 2155.62  5023.5 2156.02
  5033.7 2153.89  5053.9 2155.21  5064.0 2156.72  5074.1 2159.23  5080.6 2162.76
  5085.7 2162.32  5094.3 2163.03  5114.5 2163.10  5175.2 2161.62  5215.1 2162.22
  5225.7 2161.71  5245.9 2162.45  5289.9 2162.18  5347.0 2163.19  5442.2 2166.60
#Mann=3,-1,0
  4630.0   0.035       0  4997.1   0.035       0  5001.1   0.035       0
Bank Sta=4997.1,5001.1
Exp/Cntr=0.3,0.1

Type RM Length L Ch R = 1,3628,344,344,344
BEGIN DESCRIPTION:
Sweetwater Creek Trib 21 T2 4053
END DESCRIPTION:
XS GIS Cut Line= 3
      1379204.98      6849860.64      1379048.69      6849844.68
      1378692.12      6849756.98
#Sta/Elev= 30
  4842.9 2162.85  4918.2 2160.97  4923.3 2157.54  4983.6 2154.09  4993.7 2153.02
  5006.0 2152.70  5006.2 2152.20  5009.7 2152.20  5010.0 2152.70  5024.4 2153.58
  5035.4 2155.94  5044.4 2156.39  5049.5 2158.17  5075.9 2160.23  5132.6 2161.04
  5137.7 2160.50  5158.3 2160.66  5189.2 2159.48  5209.8 2159.40  5220.8 2157.96
  5230.4 2157.84  5251.0 2158.53  5257.2 2159.53  5262.3 2159.02  5298.7 2161.25
  5303.9 2161.02  5323.0 2162.36  5333.3 2162.45  5345.4 2163.56  5367.2 2163.73
#Mann=4,-1,0
  4842.9    0.16       0  5006.0    0.07       0  5010.0    0.16       0
  5035.4    0.07       0
Bank Sta=5006,5010
Exp/Cntr=0.3,0.1

Type RM Length L Ch R = 1,3284,123,123,123
BEGIN DESCRIPTION:
Sweetwater Creek Trib 21 T2 6.0
END DESCRIPTION:
XS GIS Cut Line= 3
      1379113.52      6849553.22      1378944.17      6849578.32
      1378820.28      6849655.95
#Sta/Elev= 30
  4828.8 2161.31  4837.4 2161.27  4847.5 2160.93  4857.6 2160.38  4867.7 2160.20
  4888.0 2159.46  4894.3 2159.04  4899.3 2158.56  4908.2 2157.00  4918.3 2153.78
  4928.4 2153.15  4948.6 2153.03  4992.4 2153.09  5012.8 2153.07  5028.1 2152.92
  5034.4 2152.73  5043.4 2152.91  5047.3 2152.72  5047.6 2152.22  5051.1 2152.22
  5051.3 2152.72  5058.0 2154.33  5064.6 2157.83  5070.5 2156.04  5079.9 2158.85
  5085.8 2157.96  5093.4 2158.88  5101.2 2158.33  5128.8 2159.03  5146.2 2159.34
#Mann=4,-1,0
  4828.8    0.16       0  4992.4    0.07       0  5047.3    0.07       0
  5051.3    0.07       0
Bank Sta=5047.3,5051.3
Exp/Cntr=0.3,0.1

Type RM Length L Ch R = 1,3161,259,259,259
BEGIN DESCRIPTION:
Sweetwater Creek Trib 21 T2 4052
END DESCRIPTION:
XS GIS Cut Line= 3
      1379000.56      6849456.57      1378862.08      6849488.00
      1378709.01      6849535.60
#Sta/Elev= 30
  4858.0 2156.57  4863.7 2157.09  4874.0 2155.96  4883.1 2155.54  4888.2 2156.30
  4894.5 2152.16  4897.0 2151.58  4904.7 2149.81  4913.0 2148.70  4913.2 2148.20
  4916.7 2148.20  4917.0 2148.70  4925.2 2149.95  4931.3 2150.36  4936.4 2152.69
  4945.7 2151.82  4966.2 2148.98  4986.8 2149.20  5007.4 2149.85  5047.3 2155.37
  5052.5 2155.59  5059.8 2156.50  5070.3 2156.83  5079.8 2158.49  5085.1 2158.37
  5101.7 2160.51  5112.1 2161.26  5143.6 2162.51  5155.4 2162.78  5160.3 2163.45
#Mann=4,-1,0
  4858.0    0.16       0  4897.0    0.07       0  4913.0    0.07       0
  4917.0    0.07       0
Bank Sta=4913,4917
Exp/Cntr=0.3,0.1

Type RM Length L Ch R = 1,2902,380,380,380
BEGIN DESCRIPTION:
Sweetwater Creek Trib 21 T2 5.0
END DESCRIPTION:
XS GIS Cut Line= 3
      1379105.01      6849438.02      1379057.19      6849331.90
      1379005.01      6849238.02
#Sta/Elev= 30
  4883.6 2157.64  4897.9 2157.23  4905.6 2156.24  4915.6 2155.60  4921.1 2155.55
  4927.5 2154.44  4938.5 2150.47  4944.2 2149.40  4949.7 2151.40  4960.4 2150.10
  4967.3 2147.92  4990.5 2147.16  4996.0 2147.33  4999.4 2146.96  5005.1 2146.96
  5010.5 2146.62  5010.7 2146.12  5014.2 2146.12  5014.5 2146.62  5018.2 2147.25
  5027.3 2146.98  5034.2 2147.20  5039.9 2147.71  5050.2 2150.12  5056.0 2151.88
  5061.7 2152.49  5072.0 2154.21  5077.7 2154.47  5104.6 2158.64  5107.4 2158.64
#Mann=3,-1,0
  4883.6    0.16       0  5010.5    0.07       0  5014.5    0.16       0
Bank Sta=5010.5,5014.5
Exp/Cntr=0.3,0.1

Type RM Length L Ch R = 1,2522,76,76,76
BEGIN DESCRIPTION:
Sweetwater Creek Trib 21 T2 4051
END DESCRIPTION:
XS GIS Cut Line= 3
      1379373.36      6849347.44      1379378.51      6849211.84
      1379330.98      6849086.34
#Sta/Elev= 30
  4864.3 2155.85  4866.5 2155.85  4883.8 2152.19  4895.1 2151.36  4903.8 2151.00
  4913.8 2150.28  4923.8 2146.58  4933.8 2144.73  4953.8 2143.21  4973.8 2142.57
  4993.8 2141.73  4998.8 2140.90  5002.7 2140.62  5003.0 2140.12  5006.5 2140.12
  5006.7 2140.62  5014.8 2140.67  5022.1 2142.12  5027.4 2140.90  5036.2 2143.44
  5046.9 2145.24  5052.2 2147.66  5057.6 2148.49  5068.3 2150.98  5089.6 2152.81
  5107.2 2153.62  5112.6 2154.54  5121.7 2154.47  5130.6 2155.10  5134.2 2155.10
#Mann=4,-1,0
  4864.3   0.035       0  4895.1    0.07       0  5002.7    0.07       0
  5006.7    0.07       0
Bank Sta=5002.7,5006.7
Exp/Cntr=0.3,0.1

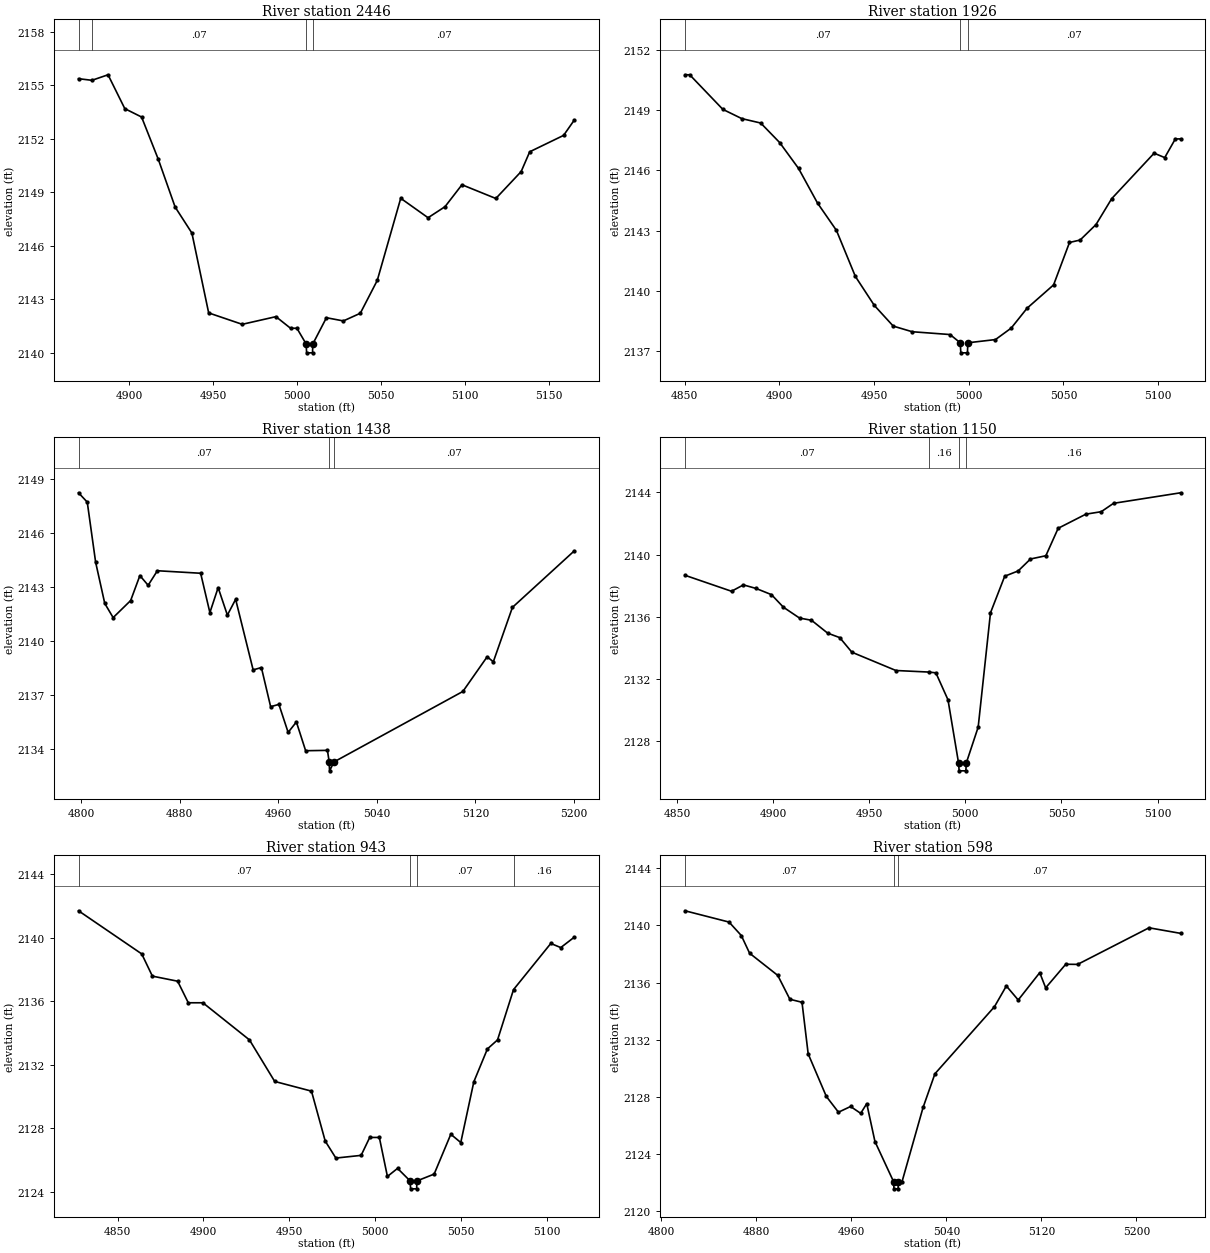
Type RM Length L Ch R = 1,2446,520,520,520
BEGIN DESCRIPTION:
Sweetwater Creek Trib 21 T2 4.0
END DESCRIPTION:
XS GIS Cut Line= 3
      1379432.79      6849335.55      1379438.32      6849205.47
      1379415.67      6849041.73
#Sta/Elev= 30
  4869.8 2155.37  4877.8 2155.28  4887.4 2155.59  4897.4 2153.69  4907.4 2153.22
  4917.4 2150.84  4927.4 2148.17  4937.4 2146.71  4947.4 2142.23  4967.4 2141.59
  4987.5 2142.02  4996.2 2141.37  5000.0 2141.37  5005.5 2140.49  5005.8 2139.99
  5009.3 2139.99  5009.5 2140.49  5017.6 2141.96  5027.7 2141.78  5037.8 2142.21
  5047.9 2144.05  5061.9 2148.66  5078.2 2147.57  5088.3 2148.19  5098.4 2149.42
  5118.6 2148.65  5133.7 2150.16  5138.8 2151.27  5159.0 2152.19  5165.3 2153.04
#Mann=4,-1,0
  4869.8   0.035       0  4877.8    0.07       0  5005.5    0.07       0
  5009.5    0.07       0
Bank Sta=5005.5,5009.5
Exp/Cntr=0.3,0.1

Type RM Length L Ch R = 1,1926,488,488,488
BEGIN DESCRIPTION:
Sweetwater Creek Trib 21 T2 3.0
END DESCRIPTION:
XS GIS Cut Line= 3
      1379855.00      6849137.98      1379855.03      6848988.08
      1379804.99      6848887.99
#Sta/Elev= 30
  4850.1 2150.75  4852.6 2150.75  4870.1 2149.03  4880.1 2148.57  4890.1 2148.35
  4900.1 2147.38  4910.1 2146.09  4920.1 2144.37  4930.1 2143.01  4940.1 2140.72
  4950.1 2139.28  4960.1 2138.25  4970.1 2137.97  4990.1 2137.83  4995.5 2137.42
  4995.8 2136.92  4999.3 2136.92  4999.5 2137.42  5014.1 2137.58  5022.4 2138.15
  5030.8 2139.14  5044.8 2140.30  5053.2 2142.41  5058.8 2142.53  5067.2 2143.30
  5075.5 2144.59  5097.9 2146.85  5103.5 2146.63  5109.1 2147.56  5111.9 2147.56
#Mann=3,-1,0
  4850.1    0.07       0  4995.5    0.07       0  4999.5    0.07       0
Bank Sta=4995.5,4999.5
Exp/Cntr=0.3,0.1

Type RM Length L Ch R = 1,1438,288,288,288
BEGIN DESCRIPTION:
Sweetwater Creek Trib 21 T2 2.0
END DESCRIPTION:
XS GIS Cut Line= 3
      1380305.02      6848838.02      1380154.63      6848703.17
      1379955.00      6848688.00
#Sta/Elev= 30
  4798.0 2148.25  4805.1 2147.73  4811.9 2144.38  4819.3 2142.09  4826.1 2141.30
  4840.3 2142.25  4847.8 2143.64  4854.5 2143.10  4862.0 2143.91  4897.1 2143.77
  4904.6 2141.58  4911.3 2142.97  4918.8 2141.44  4925.5 2142.32  4939.7 2138.39
  4946.4 2138.52  4953.9 2136.34  4960.6 2136.47  4968.1 2134.91  4974.8 2135.49
  4982.3 2133.89  5000.0 2133.91  5001.4 2133.27  5001.7 2132.77  5005.4 2133.27
  5109.9 2137.19  5129.6 2139.12  5134.6 2138.84  5150.1 2141.87  5200.2 2145.01
#Mann=3,-1,0
  4798.0    0.07       0  5001.4    0.07       0  5005.4    0.07       0
Bank Sta=5001.4,5005.4
Exp/Cntr=0.3,0.1

Type RM Length L Ch R = 1,1150,207,207,207
BEGIN DESCRIPTION:
Sweetwater Creek Trib 21 T2 4050
END DESCRIPTION:
XS GIS Cut Line= 3
      1380167.91      6848577.68      1380080.96      6848460.64
      1379993.78      6848390.33
#Sta/Elev= 30
  4854.2 2138.66  4878.4 2137.63  4884.6 2138.04  4891.2 2137.81  4899.2 2137.41
  4905.4 2136.60  4913.8 2135.90  4920.0 2135.76  4928.4 2134.93  4934.7 2134.64
  4941.0 2133.70  4963.9 2132.52  4980.9 2132.42  4984.7 2132.37  4991.0 2130.63
  4996.5 2126.55  4996.8 2126.05  5000.3 2126.05  5000.5 2126.55  5006.7 2128.87
  5013.1 2136.24  5020.5 2138.60  5027.5 2138.94  5033.9 2139.71  5041.9 2139.92
  5048.3 2141.69  5062.7 2142.60  5070.7 2142.76  5077.1 2143.30  5112.0 2143.98
#Mann=4,-1,0
  4854.2    0.07       0  4980.9    0.16       0  4996.5    0.07       0
  5000.5    0.16       0
Bank Sta=4996.5,5000.5
Exp/Cntr=0.3,0.1

Type RM Length L Ch R = 1,943,345,345,345
BEGIN DESCRIPTION:
Sweetwater Creek Trib 21 T2 1.0
END DESCRIPTION:
XS GIS Cut Line= 3
      1380405.03      6848588.02      1380264.87      6848487.12
      1380205.00      6848388.00
#Sta/Elev= 30
  4827.3 2141.70  4864.1 2138.98  4870.3 2137.58  4885.0 2137.26  4891.2 2135.90
  4899.7 2135.90  4926.8 2133.56  4941.5 2130.94  4962.9 2130.33  4970.9 2127.18
  4977.1 2126.11  4991.8 2126.28  4996.8 2127.41  5002.4 2127.41  5007.1 2124.95
  5013.0 2125.46  5020.3 2124.67  5020.6 2124.17  5024.1 2124.17  5024.3 2124.67
  5034.3 2125.10  5044.0 2127.61  5049.8 2127.09  5057.4 2130.92  5065.3 2132.99
  5071.2 2133.56  5080.5 2136.73  5102.2 2139.64  5108.0 2139.38  5115.8 2140.03
#Mann=4,-1,0
  4827.3    0.07       0  5020.3    0.07       0  5024.3    0.07       0
  5080.5    0.16       0
Bank Sta=5020.3,5024.3
Exp/Cntr=0.3,0.1

Type RM Length L Ch R = 1,598,103,103,103
BEGIN DESCRIPTION:
Sweetwater Creek Trib 21 T2 4049
END DESCRIPTION:
XS GIS Cut Line= 3
      1380631.32      6848274.86      1380455.36      6848236.92
      1380218.45      6848248.77
#Sta/Elev= 30
  4820.0 2141.02  4857.1 2140.23  4867.4 2139.29  4874.4 2138.05  4898.1 2136.50
  4908.3 2134.83  4918.5 2134.62  4923.7 2131.01  4939.0 2128.03  4949.2 2126.93
  4959.4 2127.33  4967.9 2126.85  4973.0 2127.53  4979.9 2124.88  4995.6 2122.07
  4995.9 2121.57  4999.4 2121.57  4999.6 2122.07  5002.7 2122.07  5020.4 2127.26
  5030.4 2129.62  5080.5 2134.31  5090.5 2135.76  5100.5 2134.78  5118.6 2136.69
  5123.6 2135.63  5140.5 2137.28  5150.5 2137.27  5210.6 2139.83  5237.2 2139.44
#Mann=3,-1,0
  4820.0    0.07       0  4995.6    0.07       0  4999.6    0.07       0
Bank Sta=4995.6,4999.6
Exp/Cntr=0.3,0.1

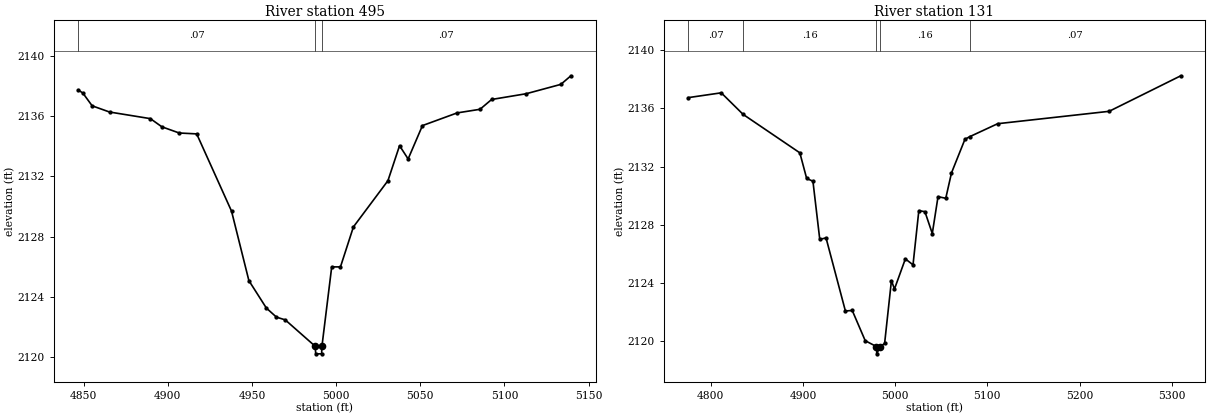
Type RM Length L Ch R = 1,495,364,364,364
BEGIN DESCRIPTION:
Sweetwater Creek Trib 21 T2 2392
END DESCRIPTION:
XS GIS Cut Line= 3
      1380602.88      6848173.65      1380454.99      6848134.06
      1380319.11      6848165.64
#Sta/Elev= 30
  4846.9 2137.72  4849.6 2137.51  4855.1 2136.67  4865.4 2136.26  4889.7 2135.82
  4896.5 2135.28  4906.8 2134.87  4917.2 2134.81  4937.9 2129.69  4948.2 2125.09
  4958.6 2123.27  4964.6 2122.67  4969.8 2122.49  4987.6 2120.74  4987.9 2120.24
  4991.4 2120.24  4991.6 2120.74  4997.4 2126.00  5002.6 2126.00  5010.3 2128.65
  5030.8 2131.71  5037.7 2134.03  5042.8 2133.15  5051.3 2135.36  5071.9 2136.20
  5085.5 2136.44  5092.4 2137.09  5112.9 2137.47  5133.5 2138.09  5139.5 2138.66
#Mann=3,-1,0
  4846.9    0.07       0  4987.6    0.07       0  4991.6    0.07       0
Bank Sta=4987.6,4991.6
Exp/Cntr=0.3,0.1

Type RM Length L Ch R = 1,131,0,0,0
BEGIN DESCRIPTION:
Sweetwater Creek Trib 21 T2 4485
END DESCRIPTION:
XS GIS Cut Line= 3
      1380621.16      6847952.90      1380455.13      6847802.09
      1380269.81      6848050.22
#Sta/Elev= 30
  4775.7 2136.74  4811.5 2137.07  4835.2 2135.59  4896.7 2132.95  4904.1 2131.19
  4910.9 2131.00  4918.3 2127.01  4925.1 2127.11  4946.1 2122.09  4953.5 2122.13
  4967.6 2120.05  4979.8 2119.65  4980.1 2119.15  4983.8 2119.65  4988.6 2119.86
  4996.0 2124.18  4999.3 2123.60  5011.1 2125.67  5019.4 2125.26  5025.7 2128.98
  5032.3 2128.91  5040.3 2127.41  5046.5 2129.94  5054.9 2129.83  5061.1 2131.57
  5075.7 2133.88  5080.9 2134.06  5111.2 2134.95  5232.0 2135.80  5309.7 2138.24
#Mann=5,-1,0
  4775.7    0.07       0  4835.2    0.16       0  4979.8    0.07       0
  4983.8    0.16       0  5080.9    0.07       0
Bank Sta=4979.8,4983.8
Exp/Cntr=0.3,0.1

Chan Stop Cuts=-1