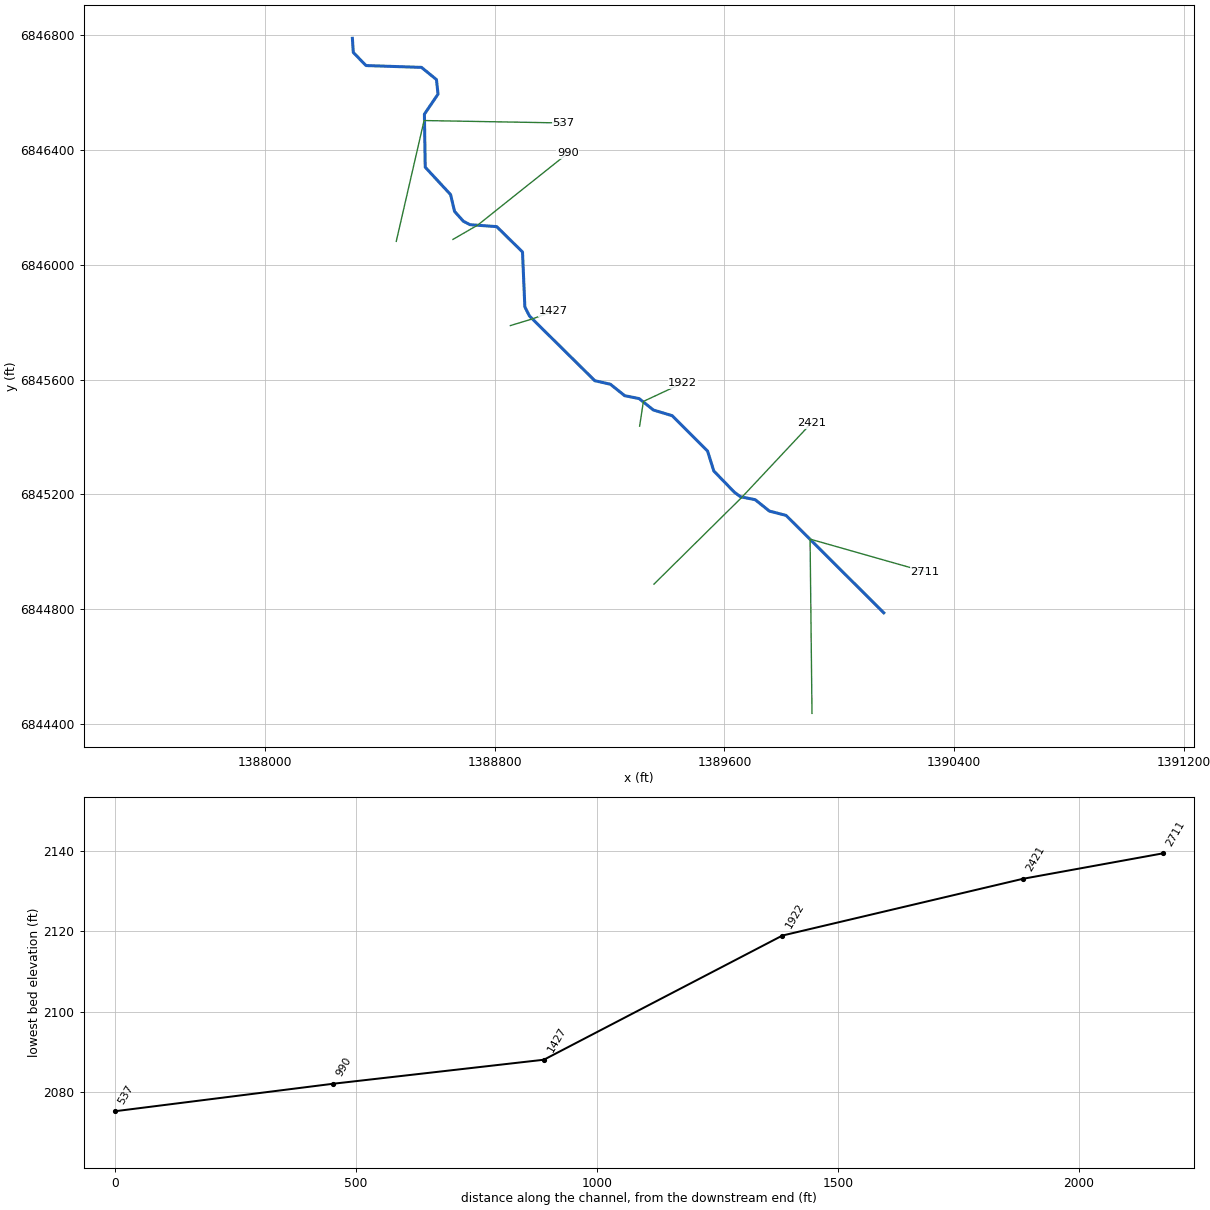
--- Sweetwater Creek Trib 22.prj (project) ---

Proj Title=Sweetwater Creek Trib 22 Base Level Engineering
Current Plan=p01
Default Exp/Contr=0.3,0.1
English Units
Geom File=g01
Flow File=f01
Plan File=p01
BEGIN DESCRIPTION:
Sweetwater Creek Trib 22
END DESCRIPTION:

--- Sweetwater Creek Trib 22.p01 (plan) ---

Plan Title=Multiple Run
Short Identifier=Multiple
Geom File=g01
Flow File=f01
Subcritical Flow
K Sum by GR= 0
Std Step Tol= 0.01
Critical Tol= 0.01
Num of Std Step Trials= 20
Max Error Tol= 0.3
Flow Tol Ratio= 0.001
Split Flow NTrial= 30
Split Flow Tol= 0.02
Split Flow Ratio= 0.02
Log Output Level= 0
Friction Slope Method= 1
Unsteady Friction Slope Method= 2
Unsteady Bridges Friction Slope Method= 1
Parabolic Critical Depth
Global Vel Dist=  1 , 1 , 1
Global Log Level= 0
CheckData=True
Encroach Param= -1, 0, 0, 0
BEGIN DESCRIPTION:
Multiple Run
END DESCRIPTION:

--- Sweetwater Creek Trib 22.f01 (steady flow) ---

Flow Title=Multiple
Number of Profiles=7
Profile Names=10-year,25-year,50-year,1pct_min,100-year,1pct_plu,500-year
River Rch & RM= Sweetwater Creek,Reach-1,2711
     299     430     542     341     680    1356    1081
Boundary for River Rch & Prof#=Sweetwater Creek,Reach-1,1
Up Type=0
Dn Type=3
Dn Slope=0.005
Boundary for River Rch & Prof#=Sweetwater Creek,Reach-1,2
Up Type=0
Dn Type=3
Dn Slope=0.005
Boundary for River Rch & Prof#=Sweetwater Creek,Reach-1,3
Up Type=0
Dn Type=3
Dn Slope=0.005
Boundary for River Rch & Prof#=Sweetwater Creek,Reach-1,4
Up Type=0
Dn Type=3
Dn Slope=0.005
Boundary for River Rch & Prof#=Sweetwater Creek,Reach-1,5
Up Type=0
Dn Type=3
Dn Slope=0.005
Boundary for River Rch & Prof#=Sweetwater Creek,Reach-1,6
Up Type=0
Dn Type=3
Dn Slope=0.005
Boundary for River Rch & Prof#=Sweetwater Creek,Reach-1,7
Up Type=0
Dn Type=3
Dn Slope=0.005

--- Sweetwater Creek Trib 22.g01 (geometry) ---

Geom Title=Existing Conditions

River Reach=Sweetwater Creek,Reach-1
Reach XY= 30
      1390155.00      6844788.00      1389814.68      6845127.24
      1389756.74      6845142.19      1389707.19      6845181.90
      1389656.62      6845191.94      1389634.87      6845207.77
      1389563.15      6845281.93      1389541.37      6845351.21
      1389418.22      6845474.38      1389352.81      6845494.10
      1389303.28      6845533.84      1389252.80      6845544.08
      1389203.26      6845583.81      1389148.94      6845596.14
      1388921.43      6845821.24      1388905.38      6845853.16
      1388897.20      6846044.21      1388807.44      6846132.48
      1388714.48      6846139.25      1388691.35      6846151.26
      1388660.74      6846185.43      1388646.81      6846244.02
      1388558.55      6846339.47      1388555.70      6846524.09
      1388603.11      6846593.77      1388597.66      6846644.39
      1388545.61      6846686.86      1388352.31      6846693.26
      1388308.12      6846738.98      1388305.00      6846788.00

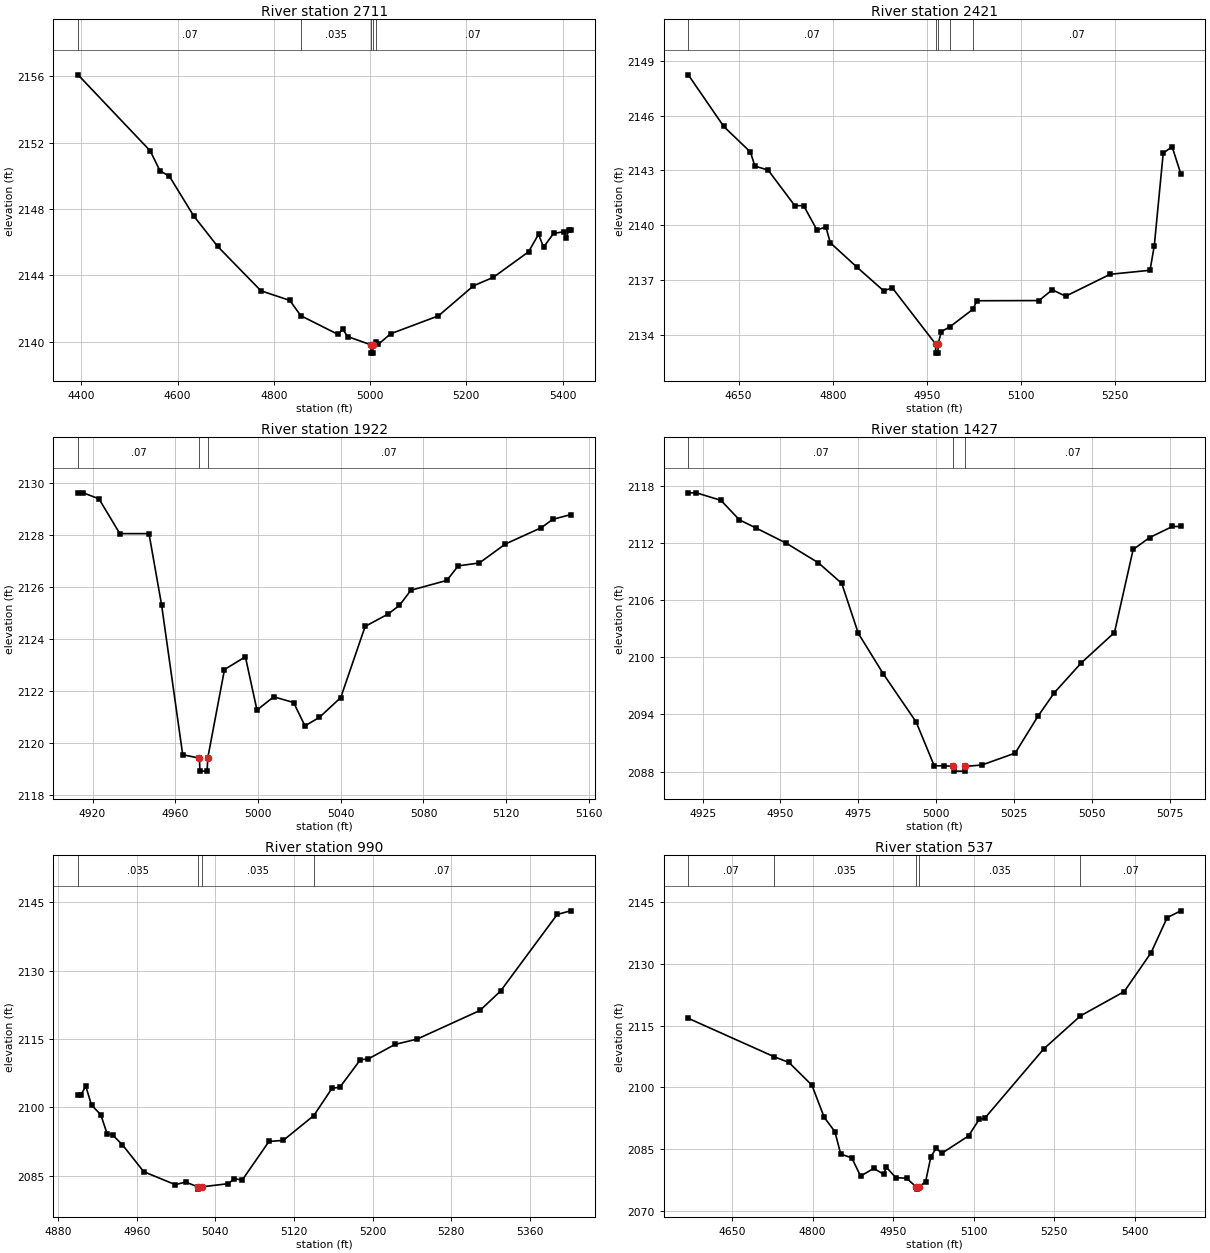
Type RM Length L Ch R = 1,2711,290,290,290
BEGIN DESCRIPTION:
Sweetwater Creek Trib 22 4.0
END DESCRIPTION:
XS GIS Cut Line= 3
      1389905.00      6844438.02      1389898.34      6845044.68
      1390299.01      6844930.94
#Sta/Elev= 30
  4393.3 2156.09  4543.3 2151.50  4563.3 2150.31  4583.3 2149.96  4633.3 2147.59
  4683.3 2145.74  4773.3 2143.06  4833.3 2142.48  4856.0 2141.56  4933.3 2140.43
  4943.3 2140.75  4953.3 2140.30  5001.9 2139.80  5002.2 2139.30  5005.7 2139.30
  5005.9 2139.80  5011.4 2140.00  5017.3 2139.84  5043.0 2140.47  5142.1 2141.55
  5214.8 2143.36  5256.4 2143.88  5329.2 2145.41  5350.0 2146.47  5360.4 2145.69
  5381.1 2146.52  5401.9 2146.62  5408.0 2146.25  5412.7 2146.74  5416.5 2146.74
#Mann=5,-1,0
  4393.3    0.07       0  4856.0   0.035       0  5001.9   0.035       0
  5005.9   0.035       0  5011.4    0.07       0
Bank Sta=5001.9,5005.9
Exp/Cntr=0.3,0.1

Type RM Length L Ch R = 1,2421,499,499,499
BEGIN DESCRIPTION:
Sweetwater Creek Trib 22 3.0
END DESCRIPTION:
XS GIS Cut Line= 3
      1389355.00      6844888.00      1389661.03      6845190.50
      1389903.26      6845449.05
#Sta/Elev= 30
  4569.7 2148.24  4626.2 2145.41  4668.7 2144.01  4675.8 2143.24  4696.9 2143.02
  4739.4 2141.07  4753.5 2141.07  4774.8 2139.73  4788.9 2139.91  4795.9 2139.04
  4838.4 2137.70  4880.8 2136.41  4894.9 2136.56  4963.7 2133.49  4963.9 2132.99
  4967.4 2132.99  4967.7 2133.49  4972.8 2134.17  4986.8 2134.44  5023.4 2135.40
  5029.3 2135.86  5128.4 2135.87  5149.5 2136.46  5170.9 2136.11  5241.8 2137.31
  5305.3 2137.53  5312.1 2138.88  5326.3 2143.95  5340.5 2144.30  5354.3 2142.82
#Mann=5,-1,0
  4569.7    0.07       0  4963.7   0.035       0  4967.7    0.07       0
  4986.8   0.035       0  5023.4    0.07       0
Bank Sta=4963.7,4967.7
Exp/Cntr=0.3,0.1

Type RM Length L Ch R = 1,1922,495,495,495
BEGIN DESCRIPTION:
Sweetwater Creek Trib 22 2.0
END DESCRIPTION:
XS GIS Cut Line= 3
      1389305.00      6845438.02      1389318.07      6845524.03
      1389454.97      6845587.98
#Sta/Elev= 30
  4913.0 2129.61  4915.5 2129.61  4923.1 2129.38  4933.2 2128.04  4947.3 2128.04
  4953.4 2125.29  4963.6 2119.53  4971.7 2119.40  4971.9 2118.90  4975.4 2118.90
  4975.7 2119.40  4983.8 2122.81  4993.9 2123.30  4999.5 2121.25  5007.6 2121.76
  5017.2 2121.54  5022.7 2120.64  5029.7 2120.97  5040.0 2121.73  5051.8 2124.47
  5062.8 2124.94  5068.4 2125.28  5073.9 2125.86  5091.3 2126.24  5096.8 2126.80
  5107.0 2126.91  5119.6 2127.64  5137.0 2128.27  5142.5 2128.59  5151.1 2128.77
#Mann=3,-1,0
  4913.0    0.07       0  4971.7    0.07       0  4975.7    0.07       0
Bank Sta=4971.7,4975.7
Exp/Cntr=0.3,0.1

Type RM Length L Ch R = 1,1427,437,437,437
BEGIN DESCRIPTION:
Sweetwater Creek Trib 22 1.0
END DESCRIPTION:
XS GIS Cut Line= 3
      1388855.00      6845788.00      1388931.17      6845811.13
      1389005.03      6845838.01
#Sta/Elev= 27
  4920.4 2117.25  4923.0 2117.25  4930.9 2116.46  4936.8 2114.42  4942.1 2113.57
  4951.8 2111.98  4962.2 2109.91  4969.7 2107.75  4975.0 2102.52  4983.1 2098.23
  4993.6 2093.21  4999.4 2088.62  5002.7 2088.62  5005.4 2088.56  5005.7 2088.06
  5009.2 2088.06  5009.4 2088.56  5014.7 2088.70  5025.4 2089.95  5032.7 2093.81
  5038.0 2096.29  5046.6 2099.40  5057.3 2102.60  5063.3 2111.31  5068.6 2112.56
  5075.9 2113.72  5078.6 2113.72
#Mann=3,-1,0
  4920.4    0.07       0  5005.4    0.07       0  5009.4    0.07       0
Bank Sta=5005.4,5009.4
Exp/Cntr=0.3,0.1

Type RM Length L Ch R = 1,990,453,453,453
BEGIN DESCRIPTION:
Sweetwater Creek Trib 22 478
END DESCRIPTION:
XS GIS Cut Line= 3
      1388654.98      6846087.99      1388741.23      6846137.79
      1389054.99      6846387.99
#Sta/Elev= 30
  4900.4 2102.77  4903.3 2102.77  4908.3 2104.66  4914.1 2100.50  4923.5 2098.43
  4929.9 2094.27  4935.6 2093.96  4945.6 2091.80  4967.2 2085.92  4999.3 2083.08
  5009.8 2083.65  5022.2 2082.60  5022.5 2082.10  5026.2 2082.60  5053.0 2083.29
  5059.4 2084.38  5067.4 2084.10  5094.6 2092.55  5109.1 2092.78  5140.2 2098.22
  5158.7 2104.20  5166.7 2104.43  5187.5 2110.45  5195.6 2110.64  5222.8 2113.82
  5245.2 2114.97  5309.2 2121.26  5330.1 2125.51  5387.7 2142.29  5401.3 2143.09
#Mann=4,-1,0
  4900.4   0.035       0  5022.2   0.035       0  5026.2   0.035       0
  5140.2    0.07       0
Bank Sta=5022.2,5026.2
Exp/Cntr=0.3,0.1

Type RM Length L Ch R = 1,537,0,0,0
BEGIN DESCRIPTION:
Sweetwater Creek Trib 22 4087
END DESCRIPTION:
XS GIS Cut Line= 3
      1388457.71      6846081.23      1388554.56      6846501.82
      1389040.39      6846493.35
#Sta/Elev= 30
  4568.4 2116.75  4728.5 2107.41  4755.9 2106.03  4798.7 2100.52  4821.6 2092.71
  4841.5 2089.23  4852.4 2083.77  4872.9 2082.88  4889.4 2078.43  4914.0 2080.32
  4932.2 2078.88  4937.4 2080.59  4955.0 2078.06  4975.0 2077.91  4993.5 2075.77
  4993.7 2075.27  4997.5 2075.77  5010.4 2077.02  5020.4 2083.18  5030.4 2085.21
  5040.4 2083.95  5090.5 2088.19  5110.5 2092.25  5120.5 2092.45  5230.5 2109.31
  5299.0 2117.34  5380.5 2123.24  5430.5 2132.68  5460.5 2141.20  5485.9 2142.85
#Mann=5,-1,0
  4568.4    0.07       0  4728.5   0.035       0  4993.5   0.035       0
  4997.5   0.035       0  5299.0    0.07       0
Bank Sta=4993.5,4997.5
Exp/Cntr=0.3,0.1

Chan Stop Cuts=-1