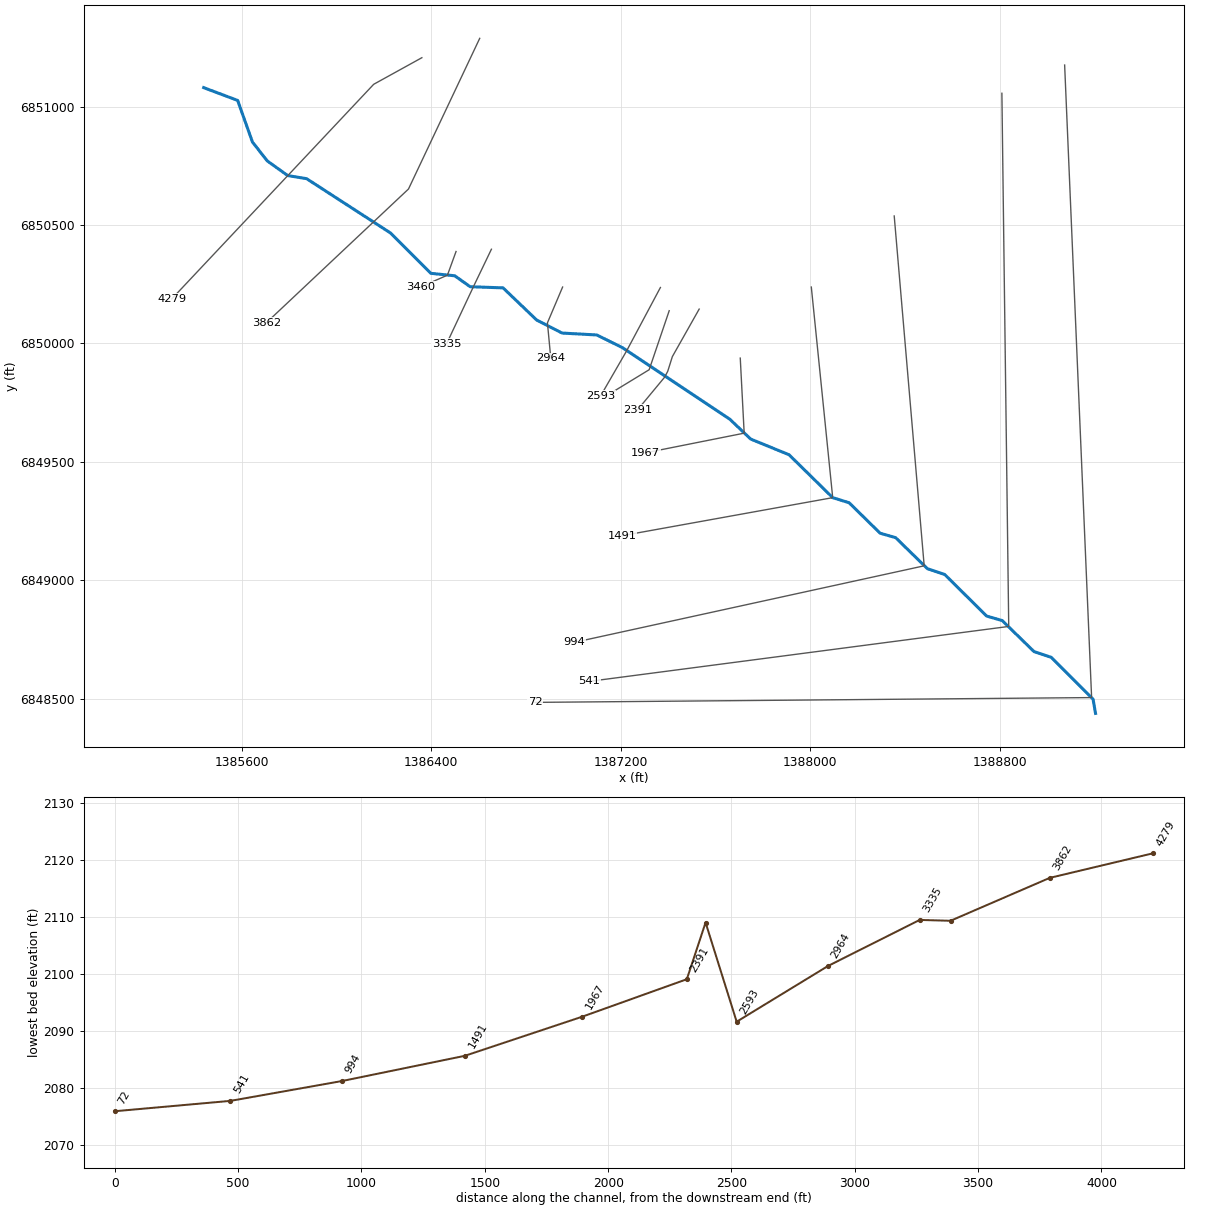
--- Sweetwater Creek Trib 23.prj (project) ---

Proj Title=Sweetwater Creek Trib 23 Base Level Engineering
Current Plan=p01
Default Exp/Contr=0.3,0.1
English Units
Geom File=g01
Flow File=f01
Plan File=p01
Y Axis Title=Elevation
X Axis Title(PF)=Main Channel Distance
X Axis Title(XS)=Station
BEGIN DESCRIPTION:
Sweetwater Creek Trib 23
END DESCRIPTION:
DSS Export Rating Curves= 0
DSS Export Rating Curve Sorted= 0
DSS Export Volume Flow Curves= 0
DXF OffsetX= 0
DXF OffsetY= 0
DXF ScaleX= 1
DXF ScaleY= 10

--- Sweetwater Creek Trib 23.p01 (plan) ---

Plan Title=Multiple Run
Short Identifier=Multiple
Geom File=g01
Flow File=f01
Subcritical Flow
K Sum by GR= 0
Std Step Tol= 0.01
Critical Tol= 0.01
Num of Std Step Trials= 20
Max Error Tol= 0.3
Flow Tol Ratio= 0.001
Split Flow NTrial= 30
Split Flow Tol= 0.02
Split Flow Ratio= 0.02
Log Output Level= 0
Friction Slope Method= 1
Unsteady Friction Slope Method= 2
Unsteady Bridges Friction Slope Method= 1
Parabolic Critical Depth
Global Vel Dist=  1 , 1 , 1
Global Log Level= 0
CheckData=True
Encroach Param= -1, 0, 0, 0
BEGIN DESCRIPTION:
Multiple Run
END DESCRIPTION:

--- Sweetwater Creek Trib 23.f01 (steady flow) ---

Flow Title=Multiple
Program Version=4.10
Number of Profiles= 7
Profile Names=10-year,25-year,50-year,1pct_min,100-year,1pct_plu,500-year
River Rch & RM=Sweetwater Creek,Reach-1         ,4279
     150     206     252     154     307     612     460
Boundary for River Rch & Prof#=Sweetwater Creek,Reach-1         , 1
Up Type= 0
Dn Type= 3
Dn Slope=0.005
Boundary for River Rch & Prof#=Sweetwater Creek,Reach-1         , 2
Up Type= 0
Dn Type= 3
Dn Slope=0.005
Boundary for River Rch & Prof#=Sweetwater Creek,Reach-1         , 3
Up Type= 0
Dn Type= 3
Dn Slope=0.005
Boundary for River Rch & Prof#=Sweetwater Creek,Reach-1         , 4
Up Type= 0
Dn Type= 3
Dn Slope=0.005
Boundary for River Rch & Prof#=Sweetwater Creek,Reach-1         , 5
Up Type= 0
Dn Type= 3
Dn Slope=0.005
Boundary for River Rch & Prof#=Sweetwater Creek,Reach-1         , 6
Up Type= 0
Dn Type= 3
Dn Slope=0.005
Boundary for River Rch & Prof#=Sweetwater Creek,Reach-1         , 7
Up Type= 0
Dn Type= 3
Dn Slope=0.005
DSS Import GetInterval= 0
DSS Import GetPeak= 0
DSS Import FillOption= 0

--- Sweetwater Creek Trib 23.g01 (geometry) ---

Geom Title=Existing Conditions

River Reach=Sweetwater Creek,Reach-1
Reach XY= 30
      1385439.49      6851079.93      1385583.04      6851025.83
      1385645.54      6850850.05      1385707.78      6850770.63
      1385794.63      6850708.43      1385873.92      6850695.63
      1386228.61      6850465.94      1386398.81      6850295.85
      1386499.43      6850285.53      1386564.67      6850239.39
      1386703.53      6850234.46      1386845.32      6850098.76
      1386952.65      6850043.71      1387099.48      6850035.64
      1387207.29      6849982.16      1387661.04      6849679.82
      1387748.95      6849596.16      1387911.06      6849529.86
      1388095.32      6849348.78      1388164.68      6849327.22
      1388295.32      6849198.78      1388361.05      6849179.84
      1388495.32      6849048.78      1388568.21      6849024.37
      1388745.32      6848848.78      1388811.05      6848829.84
      1388945.32      6848698.78      1389018.21      6848674.37
      1389194.49      6848497.79      1389205.00      6848438.00

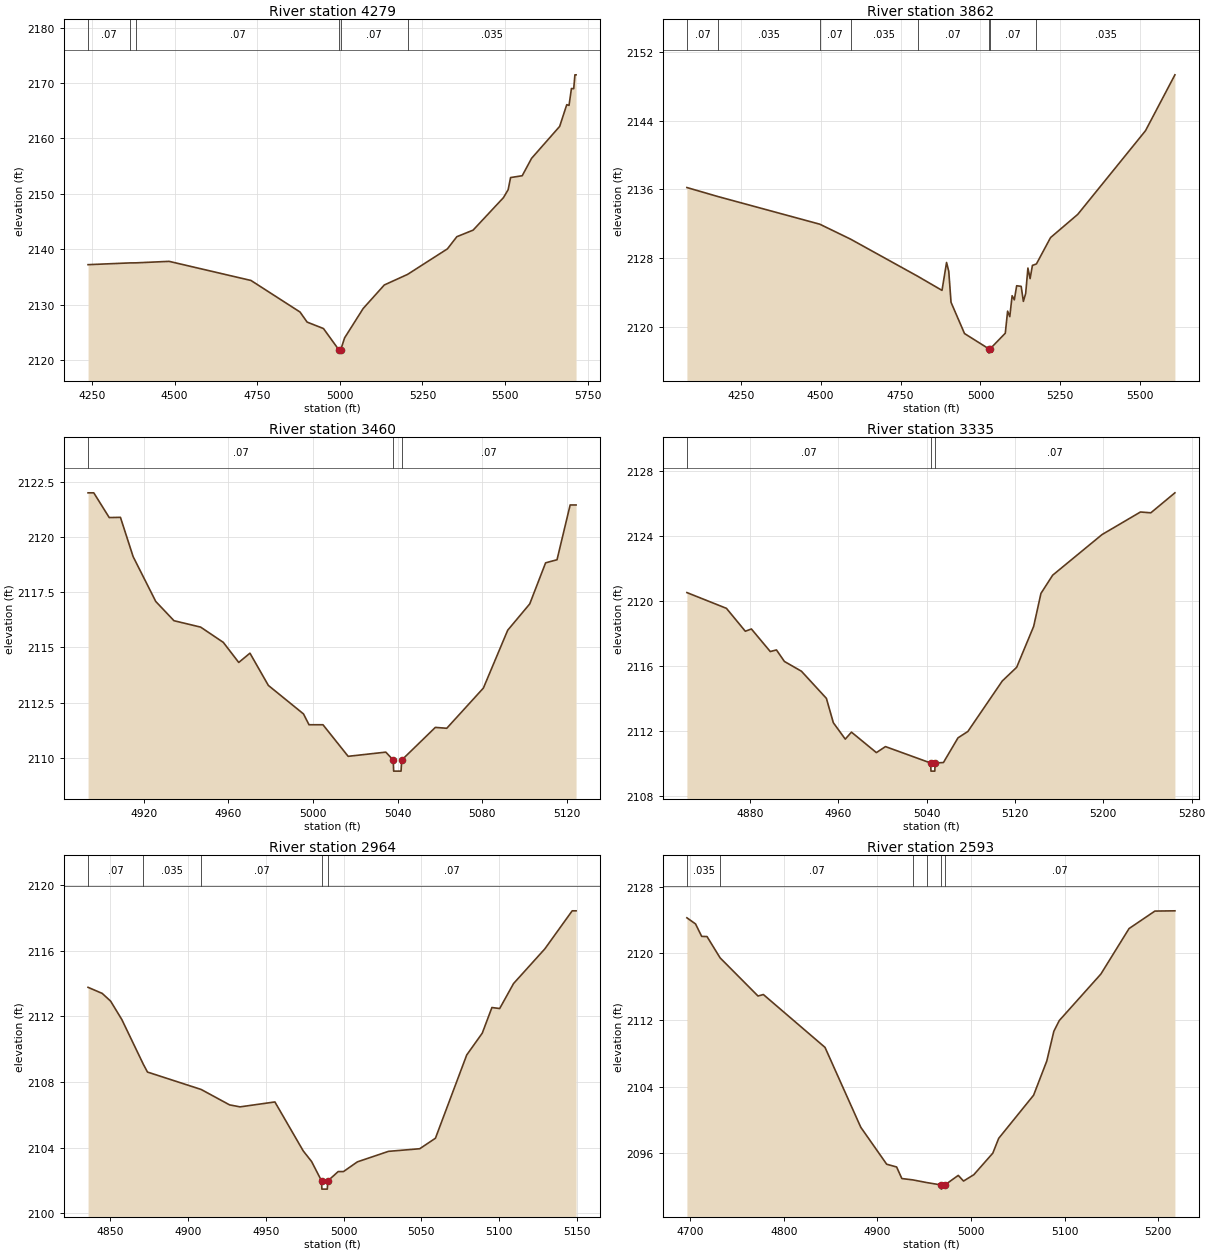
Type RM Length L Ch R = 1,4279,417,417,417
BEGIN DESCRIPTION:
Sweetwater Creek Trib 23 7.0
END DESCRIPTION:
XS GIS Cut Line= 3
      1386360.67      6851206.22      1386157.34      6851093.97
      1385304.97      6850187.97
#Sta/Elev= 30
  4238.4 2137.20  4364.4 2137.52  4383.3 2137.53  4483.5 2137.80  4731.2 2134.35
  4879.6 2128.65  4901.1 2126.83  4950.5 2125.67  4998.2 2121.73  4998.5 2121.23
  5002.2 2121.73  5014.3 2123.97  5070.6 2129.29  5134.6 2133.54  5204.7 2135.44
  5325.5 2140.06  5353.9 2142.25  5403.2 2143.44  5495.0 2149.31  5509.2 2150.75
  5516.5 2152.93  5551.7 2153.26  5580.0 2156.40  5665.0 2162.17  5686.4 2166.09
  5693.3 2165.96  5700.6 2169.01  5707.5 2168.98  5711.1 2171.48  5714.6 2171.48
#Mann=6,-1,0
  4238.4    0.07       0  4364.4   0.035       0  4383.3    0.07       0
  4998.2    0.07       0  5002.2    0.07       0  5204.7   0.035       0
Bank Sta=4998.2,5002.2
Exp/Cntr=0.3,0.1

Type RM Length L Ch R = 1,3862,402,402,402
BEGIN DESCRIPTION:
Sweetwater Creek Trib 23 6.0
END DESCRIPTION:
XS GIS Cut Line= 3
      1386605.01      6851288.02      1386304.31      6850651.92
      1385705.00      6850088.00
#Sta/Elev= 30
  4081.8 2136.22  4178.9 2135.17  4497.4 2131.95  4593.7 2130.21  4803.5 2125.89
  4879.8 2124.24  4894.0 2127.49  4900.9 2126.46  4908.0 2122.85  4950.2 2119.21
  5026.3 2117.43  5026.6 2116.93  5030.3 2117.43  5077.7 2119.25  5085.0 2121.82
  5091.8 2121.18  5099.1 2123.62  5106.0 2123.14  5113.3 2124.78  5127.4 2124.71
  5134.3 2122.96  5141.5 2123.88  5148.5 2126.84  5155.3 2125.61  5162.6 2127.15
  5175.1 2127.32  5219.3 2130.39  5304.3 2133.09  5516.3 2142.84  5608.3 2149.35
#Mann=8,-1,0
  4081.8    0.07       0  4178.9   0.035       0  4497.4    0.07       0
  4593.7   0.035       0  4803.5    0.07       0  5026.3    0.07       0
  5030.3    0.07       0  5175.1   0.035       0
Bank Sta=5026.3,5030.3
Exp/Cntr=0.3,0.1

Type RM Length L Ch R = 1,3460,125,125,125
BEGIN DESCRIPTION:
Sweetwater Creek Trib 23 5.0
END DESCRIPTION:
XS GIS Cut Line= 3
      1386505.01      6850388.03      1386468.69      6850288.13
      1386354.96      6850237.98
#Sta/Elev= 30
  4893.7 2122.00  4896.4 2122.00  4903.7 2120.88  4909.0 2120.89  4915.0 2119.11
  4925.7 2117.08  4934.3 2116.21  4946.9 2115.92  4957.6 2115.23  4964.9 2114.32
  4970.2 2114.74  4978.9 2113.28  4995.5 2111.99  4998.1 2111.50  5004.7 2111.50
  5016.6 2110.07  5034.4 2110.26  5037.9 2109.90  5038.1 2109.40  5041.6 2109.40
  5041.9 2109.90  5057.8 2111.38  5063.2 2111.34  5080.5 2113.16  5092.0 2115.78
  5102.4 2116.97  5109.9 2118.83  5115.3 2118.97  5121.5 2121.45  5124.3 2121.45
#Mann=3,-1,0
  4893.7    0.07       0  5037.9    0.07       0  5041.9    0.07       0
Bank Sta=5037.9,5041.9
Exp/Cntr=0.3,0.1

Type RM Length L Ch R = 1,3335,371,371,371
BEGIN DESCRIPTION:
Sweetwater Creek Trib 23 4486
END DESCRIPTION:
XS GIS Cut Line= 3
      1386654.36      6850397.58      1386577.70      6850237.93
      1386465.11      6849998.25
#Sta/Elev= 30
  4822.9 2120.54  4858.7 2119.57  4875.8 2118.16  4881.3 2118.30  4898.4 2116.91
  4904.0 2117.01  4911.2 2116.30  4926.6 2115.70  4949.2 2114.03  4955.5 2112.53
  4966.3 2111.52  4971.9 2111.95  4994.5 2110.69  5002.7 2111.06  5043.6 2110.05
  5043.9 2109.55  5047.4 2109.55  5047.6 2110.05  5055.2 2110.08  5068.4 2111.60
  5077.3 2111.99  5108.5 2115.10  5121.5 2115.94  5136.9 2118.46  5143.5 2120.49
  5154.1 2121.61  5198.8 2124.11  5233.6 2125.50  5243.0 2125.45  5264.8 2126.68
#Mann=3,-1,0
  4822.9    0.07       0  5043.6    0.07       0  5047.6    0.07       0
Bank Sta=5043.6,5047.6
Exp/Cntr=0.3,0.1

Type RM Length L Ch R = 1,2964,371,371,371
BEGIN DESCRIPTION:
Sweetwater Creek Trib 23 4.0
END DESCRIPTION:
XS GIS Cut Line= 3
      1386954.99      6850237.98      1386890.87      6850086.82
      1386905.00      6849937.99
#Sta/Elev= 30
  4835.8 2113.77  4844.9 2113.40  4850.3 2112.93  4857.5 2111.81  4871.4 2109.07
  4874.0 2108.61  4908.5 2107.55  4926.8 2106.61  4933.5 2106.49  4955.9 2106.79
  4974.1 2103.81  4979.5 2103.16  4985.9 2101.98  4986.1 2101.48  4989.6 2101.48
  4989.9 2101.98  4996.6 2102.55  5000.0 2102.55  5008.9 2103.14  5028.9 2103.78
  5049.0 2103.94  5059.1 2104.58  5079.2 2109.65  5089.2 2110.98  5095.4 2112.54
  5100.4 2112.48  5109.3 2114.00  5129.4 2116.11  5147.0 2118.43  5149.5 2118.43
#Mann=5,-1,0
  4835.8    0.07       0  4871.4   0.035       0  4908.5    0.07       0
  4985.9    0.07       0  4989.9    0.07       0
Bank Sta=4985.9,4989.9
Exp/Cntr=0.3,0.1

Type RM Length L Ch R = 1,2593,126,126,126
BEGIN DESCRIPTION:
Sweetwater Creek Trib 23 4489
END DESCRIPTION:
XS GIS Cut Line= 3
      1387367.88      6850236.09      1387225.07      6849968.18
      1387116.13      6849779.46
#Sta/Elev= 30
  4696.4 2124.26  4705.6 2123.53  4712.2 2122.03  4717.9 2122.01  4731.9 2119.45
  4772.4 2114.87  4778.1 2115.05  4844.0 2108.70  4882.2 2099.11  4909.9 2094.67
  4920.5 2094.34  4926.1 2092.95  4937.8 2092.79  4952.6 2092.47  4968.1 2092.18
  4968.3 2091.68  4972.1 2092.18  4986.4 2093.33  4992.0 2092.65  5003.0 2093.41
  5023.3 2096.00  5029.6 2097.78  5066.9 2102.96  5081.0 2107.07  5088.5 2110.63
  5094.3 2111.92  5138.8 2117.51  5168.9 2122.97  5196.5 2125.07  5217.9 2125.10
#Mann=6,-1,0
  4696.4   0.035       0  4731.9    0.07       0  4937.8   0.035       0
  4952.6    0.07       0  4968.1    0.07       0  4972.1    0.07       0
Bank Sta=4968.1,4972.1
Exp/Cntr=0.3,0.1

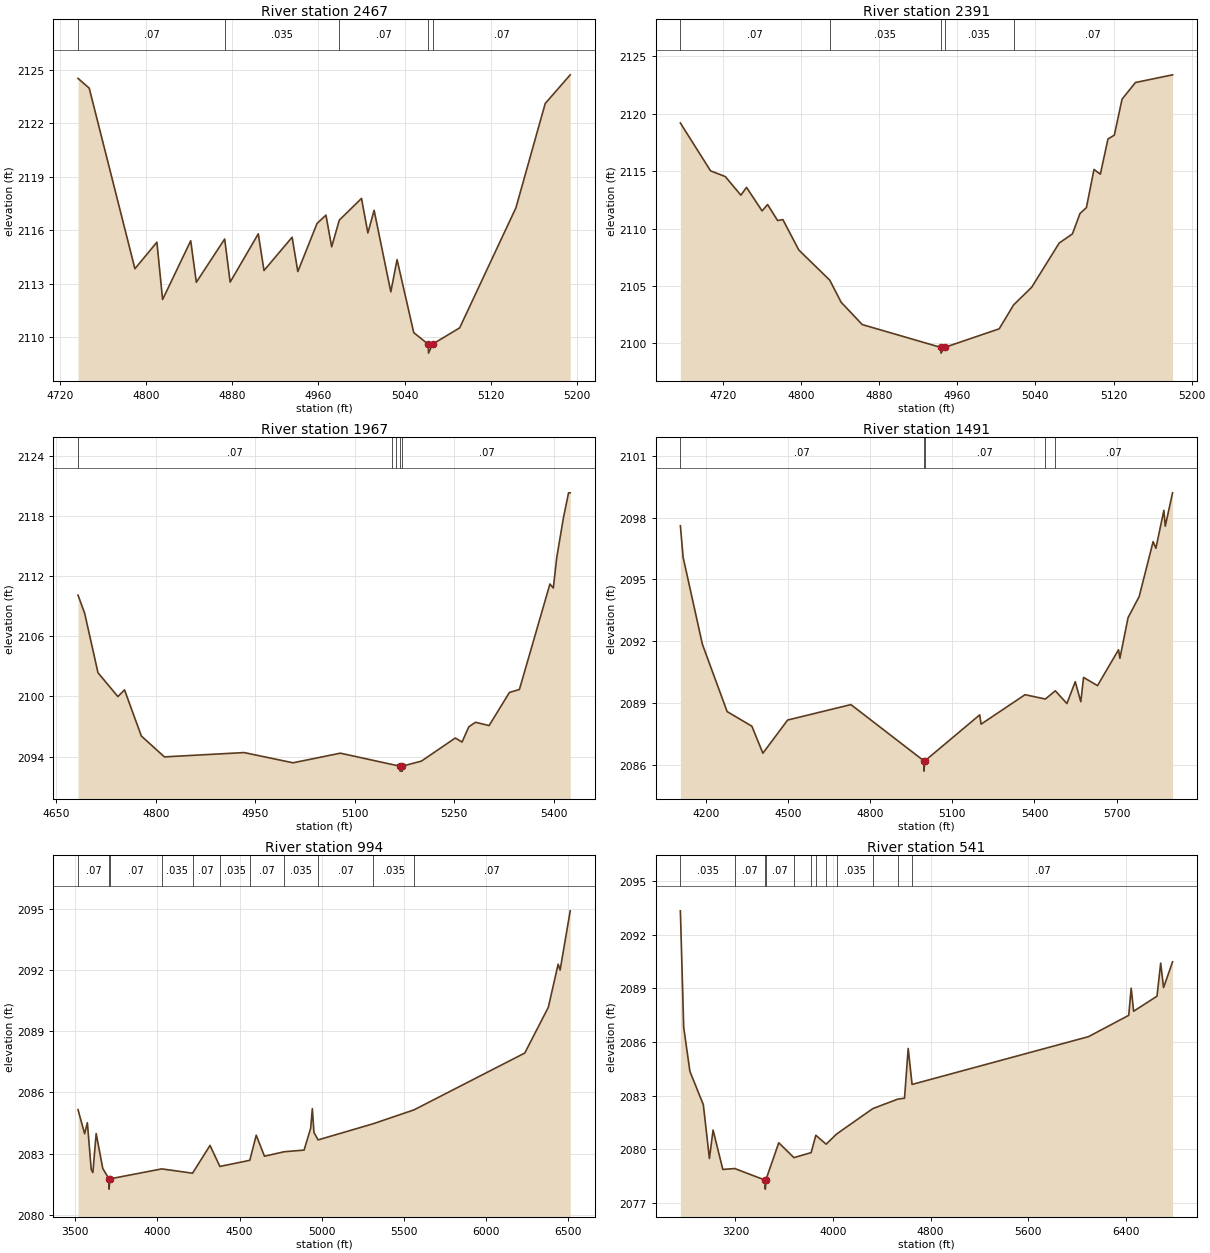
Type RM Length L Ch R = 1,2467,76,76,76
BEGIN DESCRIPTION:
Sweetwater Creek Trib 23 3.0
END DESCRIPTION:
XS GIS Cut Line= 3
      1387405.00      6850137.99      1387320.36      6849888.88
      1387155.00      6849788.00
#Sta/Elev= 30
  4736.9 2124.52  4747.3 2123.97  4789.7 2113.83  4810.1 2115.32  4815.4 2112.10
  4841.5 2115.40  4846.7 2113.07  4873.0 2115.50  4878.1 2113.08  4904.2 2115.79
  4909.5 2113.73  4935.6 2115.60  4940.9 2113.67  4958.7 2116.37  4967.0 2116.84
  4972.3 2115.06  4979.4 2116.56  5000.0 2117.78  5005.9 2115.84  5011.7 2117.11
  5027.2 2112.53  5033.0 2114.34  5048.5 2110.24  5061.9 2109.59  5062.2 2109.09
  5065.9 2109.59  5091.1 2110.51  5143.3 2117.25  5170.5 2123.11  5193.7 2124.72
#Mann=5,-1,0
  4736.9    0.07       0  4873.0   0.035       0  4979.4    0.07       0
  5061.9    0.07       0  5065.9    0.07       0
Bank Sta=5061.9,5065.9
Exp/Cntr=0.3,0.1

Type RM Length L Ch R = 1,2391,424,424,424
BEGIN DESCRIPTION:
Sweetwater Creek Trib 23 4488
END DESCRIPTION:
XS GIS Cut Line= 5
      1387531.58      6850144.93      1387418.28      6849944.21
      1387398.84      6849882.40      1387385.83      6849857.59
      1387270.66      6849718.73
#Sta/Elev= 30
  4676.7 2119.20  4707.6 2115.03  4722.7 2114.53  4738.6 2112.91  4744.4 2113.59
  4760.3 2111.54  4766.0 2112.09  4776.2 2110.70  4781.6 2110.78  4797.9 2108.13
  4829.6 2105.50  4841.2 2103.58  4862.8 2101.63  4943.2 2099.64  4943.4 2099.14
  4947.2 2099.64  5003.0 2101.26  5017.7 2103.34  5036.2 2104.88  5064.4 2108.74
  5077.9 2109.53  5085.7 2111.32  5092.2 2111.82  5100.0 2115.15  5106.5 2114.74
  5114.3 2117.81  5120.8 2118.14  5128.7 2121.28  5142.4 2122.73  5180.4 2123.40
#Mann=5,-1,0
  4676.7    0.07       0  4829.6   0.035       0  4943.2   0.035       0
  4947.2   0.035       0  5017.7    0.07       0
Bank Sta=4943.2,4947.2
Exp/Cntr=0.3,0.1

Type RM Length L Ch R = 1,1967,476,476,476
BEGIN DESCRIPTION:
Sweetwater Creek Trib 23 2.0
END DESCRIPTION:
XS GIS Cut Line= 3
      1387705.00      6849938.01      1387721.55      6849621.04
      1387305.04      6849538.01
#Sta/Elev= 30
  4682.6 2110.10  4692.6 2108.30  4712.7 2102.37  4742.7 2099.99  4752.7 2100.66
  4778.1 2096.06  4812.8 2093.98  4933.0 2094.41  5006.7 2093.39  5078.1 2094.35
  5156.2 2093.22  5162.2 2093.14  5167.8 2093.06  5168.1 2092.56  5171.6 2092.56
  5171.8 2093.06  5200.4 2093.56  5251.4 2095.86  5261.6 2095.46  5271.8 2096.98
  5282.0 2097.43  5302.4 2097.10  5333.0 2100.40  5348.1 2100.70  5394.1 2111.21
  5399.2 2110.81  5404.4 2113.86  5414.5 2117.83  5422.2 2120.30  5424.7 2120.30
#Mann=5,-1,0
  4682.6    0.07       0  5156.2   0.035       0  5162.2    0.07       0
  5167.8    0.07       0  5171.8    0.07       0
Bank Sta=5167.8,5171.8
Exp/Cntr=0.3,0.1

Type RM Length L Ch R = 1,1491,497,497,497
BEGIN DESCRIPTION:
Sweetwater Creek Trib 23 1.0
END DESCRIPTION:
XS GIS Cut Line= 3
      1388005.00      6850238.00      1388095.32      6849348.78
      1387205.02      6849188.00
#Sta/Elev= 30
  4106.2 2097.60  4116.3 2096.07  4186.6 2091.85  4277.1 2088.58  4367.5 2087.87
  4407.7 2086.56  4498.2 2088.17  4729.4 2088.92  4995.9 2086.19  4996.1 2085.69
  4999.9 2086.19  5199.9 2088.42  5205.0 2087.97  5365.6 2089.40  5439.9 2089.19
  5476.2 2089.59  5518.6 2088.97  5549.1 2090.03  5569.4 2089.06  5579.5 2090.24
  5630.4 2089.84  5707.2 2091.58  5712.3 2091.17  5742.1 2093.14  5782.8 2094.17
  5833.6 2096.83  5843.8 2096.51  5872.9 2098.35  5878.0 2097.58  5904.7 2099.20
#Mann=5,-1,0
  4106.2    0.07       0  4995.9    0.07       0  4999.9    0.07       0
  5439.9   0.035       0  5476.2    0.07       0
Bank Sta=4995.9,4999.9
Exp/Cntr=0.3,0.1

Type RM Length L Ch R = 1,994,453,453,453
BEGIN DESCRIPTION:
Sweetwater Creek Trib 23 470
END DESCRIPTION:
XS GIS Cut Line= 3
      1388355.00      6850538.01      1388481.54      6849061.02
      1387004.96      6848737.99
#Sta/Elev= 30
  3517.6 2085.16  3557.8 2083.98  3574.5 2084.52  3597.9 2082.23  3607.9 2082.08
  3628.0 2083.99  3668.2 2082.28  3706.3 2081.77  3706.6 2081.27  3710.3 2081.77
  4027.0 2082.26  4214.3 2082.05  4320.5 2083.41  4380.5 2082.38  4562.5 2082.68
  4601.6 2083.91  4651.7 2082.88  4771.5 2083.10  4892.6 2083.18  4932.8 2084.25
  4942.8 2085.21  4952.8 2084.04  4978.2 2083.68  5313.2 2084.47  5561.5 2085.15
  6235.1 2087.93  6378.4 2090.17  6438.0 2092.28  6450.0 2091.99  6511.5 2094.89
#Mann=11,-1,0
  3517.6    0.07       0  3706.3    0.07       0  3710.3    0.07       0
  4027.0   0.035       0  4214.3    0.07       0  4380.5   0.035       0
  4562.5    0.07       0  4771.5   0.035       0  4978.2    0.07       0
  5313.2   0.035       0  5561.5    0.07       0
Bank Sta=3706.3,3710.3
Exp/Cntr=0.3,0.1

Type RM Length L Ch R = 1,541,469,469,469
BEGIN DESCRIPTION:
Sweetwater Creek Trib 23 4487
END DESCRIPTION:
XS GIS Cut Line= 3
      1388809.59      6851056.15      1388838.49      6848805.04
      1387068.40      6848573.21
#Sta/Elev= 30
  2748.7 2093.33  2776.1 2086.82  2826.9 2084.36  2936.9 2082.50  2986.9 2079.49
  3016.9 2081.08  3096.9 2078.88  3194.9 2078.93  3444.9 2078.28  3445.2 2077.78
  3448.9 2078.28  3555.7 2080.37  3679.9 2079.54  3821.2 2079.82  3859.6 2080.79
  3944.1 2080.29  4030.1 2080.86  4327.1 2082.28  4532.1 2082.81  4587.0 2082.86
  4617.0 2085.64  4649.0 2083.63  6095.8 2086.30  6425.6 2087.49  6445.7 2089.01
  6465.9 2087.72  6657.5 2088.56  6687.8 2090.41  6711.4 2089.04  6785.2 2090.48
#Mann=12,-1,0
  2748.7   0.035       0  3194.9    0.07       0  3444.9    0.07       0
  3448.9    0.07       0  3679.9   0.035       0  3821.2    0.07       0
  3859.6   0.035       0  3944.1    0.07       0  4030.1   0.035       0
  4327.1    0.07       0  4532.1   0.035       0  4649.0    0.07       0
Bank Sta=3444.9,3448.9
Exp/Cntr=0.3,0.1

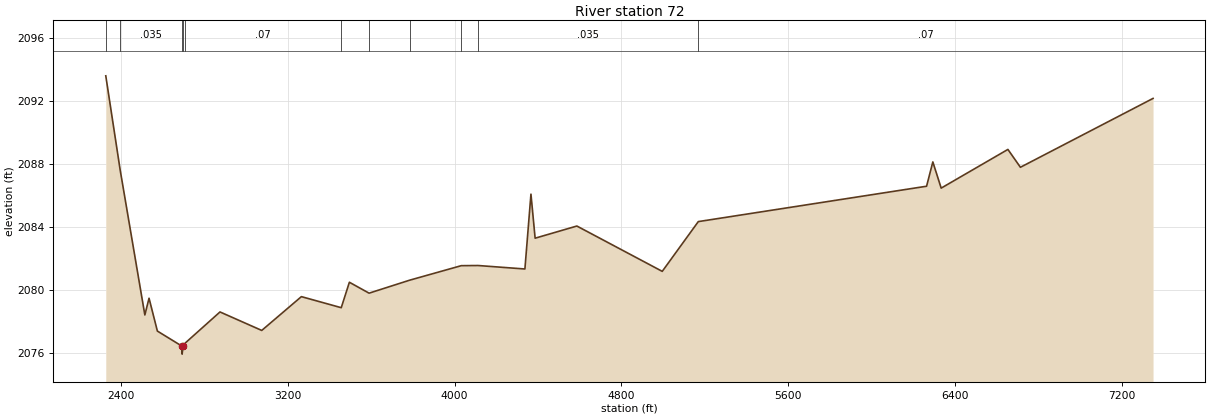
Type RM Length L Ch R = 1,72,0,0,0
BEGIN DESCRIPTION:
Sweetwater Creek Trib 23 4490
END DESCRIPTION:
XS GIS Cut Line= 3
      1389074.52      6851175.28      1389188.42      6848504.70
      1386838.91      6848484.44
#Sta/Elev= 30
  2327.0 2093.58  2396.0 2087.62  2514.4 2078.44  2534.5 2079.50  2574.5 2077.42
  2693.0 2076.46  2693.2 2075.96  2697.0 2076.46  2708.7 2076.67  2874.8 2078.63
  3075.0 2077.46  3265.1 2079.60  3456.3 2078.90  3495.3 2080.51  3589.8 2079.82
  3784.0 2080.64  4031.9 2081.56  4112.6 2081.57  4337.1 2081.35  4366.1 2086.09
  4386.1 2083.30  4586.3 2084.07  4995.8 2081.20  5168.7 2084.35  6263.5 2086.59
  6293.5 2088.13  6333.5 2086.47  6653.5 2088.92  6713.5 2087.79  7349.6 2092.15
#Mann=11,-1,0
  2327.0    0.07       0  2396.0   0.035       0  2693.0   0.035       0
  2697.0   0.035       0  2708.7    0.07       0  3456.3   0.035       0
  3589.8    0.07       0  3784.0   0.035       0  4031.9    0.07       0
  4112.6   0.035       0  5168.7    0.07       0
Bank Sta=2693,2697
Exp/Cntr=0.3,0.1

Chan Stop Cuts=-1