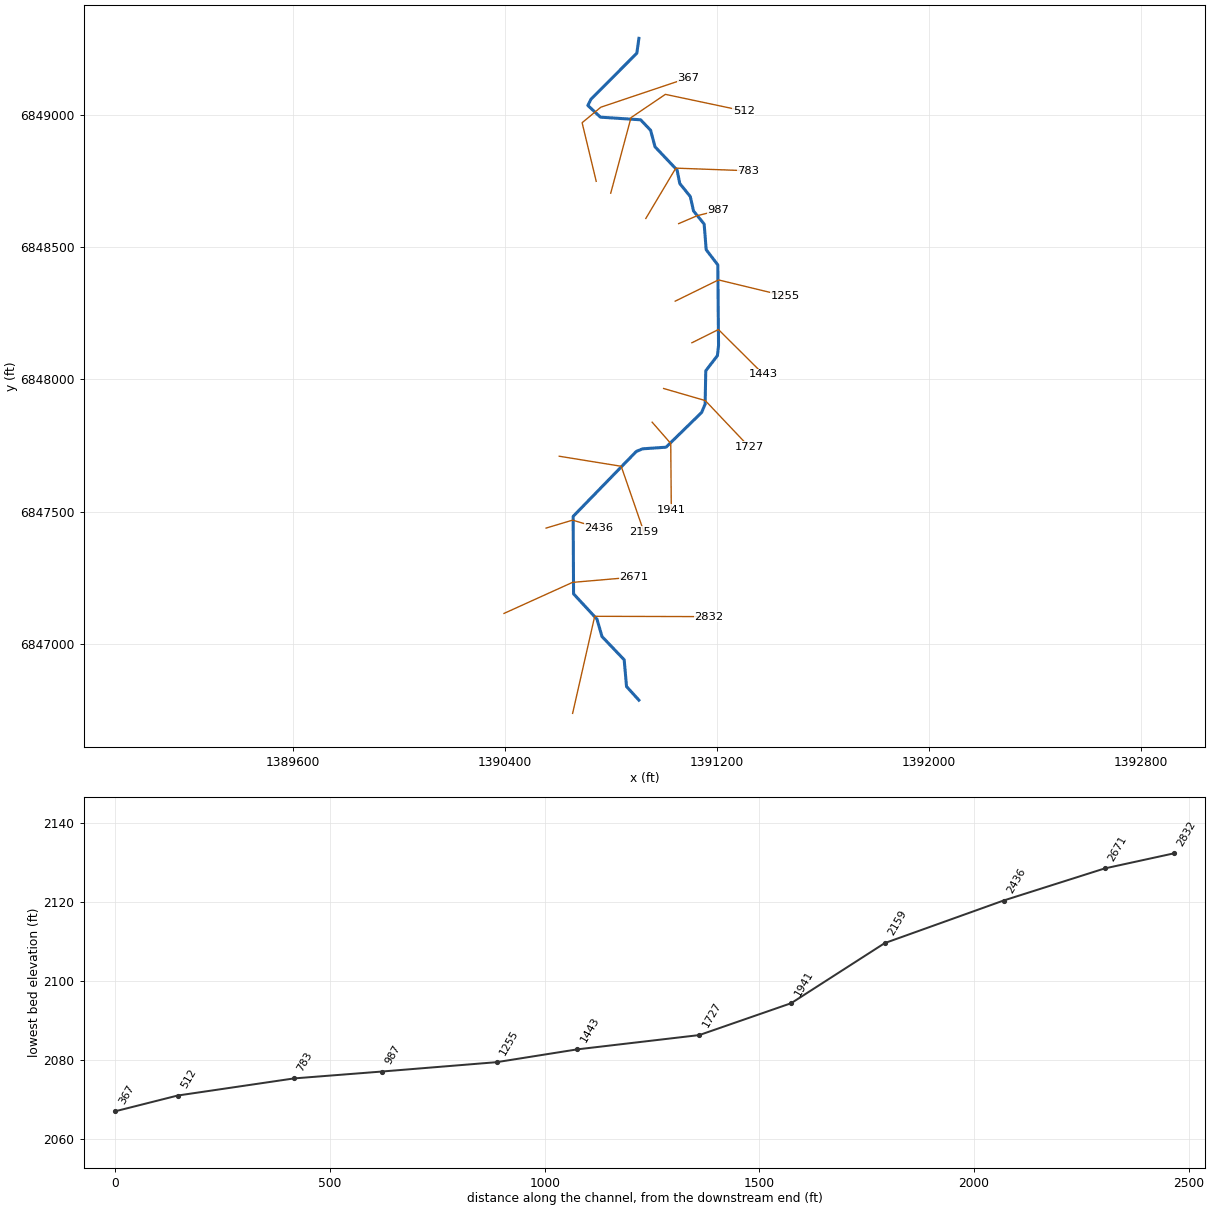
--- Sweetwater Creek Trib 24.prj (project) ---

Proj Title=Sweetwater Creek Trib 24 Base Level Engineering
Current Plan=p01
Default Exp/Contr=0.3,0.1
English Units
Geom File=g01
Flow File=f01
Plan File=p01
BEGIN DESCRIPTION:
Sweetwater Creek Trib 24
END DESCRIPTION:

--- Sweetwater Creek Trib 24.p01 (plan) ---

Plan Title=Multiple Run
Short Identifier=Multiple
Geom File=g01
Flow File=f01
Subcritical Flow
K Sum by GR= 0
Std Step Tol= 0.01
Critical Tol= 0.01
Num of Std Step Trials= 20
Max Error Tol= 0.3
Flow Tol Ratio= 0.001
Split Flow NTrial= 30
Split Flow Tol= 0.02
Split Flow Ratio= 0.02
Log Output Level= 0
Friction Slope Method= 1
Unsteady Friction Slope Method= 2
Unsteady Bridges Friction Slope Method= 1
Parabolic Critical Depth
Global Vel Dist=  1 , 1 , 1
Global Log Level= 0
CheckData=True
Encroach Param= -1, 0, 0, 0
BEGIN DESCRIPTION:
Multiple Run
END DESCRIPTION:

--- Sweetwater Creek Trib 24.f01 (steady flow) ---

Flow Title=Multiple
Number of Profiles=7
Profile Names=10-year,25-year,50-year,1pct_min,100-year,1pct_plu,500-year
River Rch & RM= Sweetwater Creek,Reach-1,2832
      91     122     146      88     175     349     253
Boundary for River Rch & Prof#=Sweetwater Creek,Reach-1,1
Up Type=0
Dn Type=3
Dn Slope=0.005
Boundary for River Rch & Prof#=Sweetwater Creek,Reach-1,2
Up Type=0
Dn Type=3
Dn Slope=0.005
Boundary for River Rch & Prof#=Sweetwater Creek,Reach-1,3
Up Type=0
Dn Type=3
Dn Slope=0.005
Boundary for River Rch & Prof#=Sweetwater Creek,Reach-1,4
Up Type=0
Dn Type=3
Dn Slope=0.005
Boundary for River Rch & Prof#=Sweetwater Creek,Reach-1,5
Up Type=0
Dn Type=3
Dn Slope=0.005
Boundary for River Rch & Prof#=Sweetwater Creek,Reach-1,6
Up Type=0
Dn Type=3
Dn Slope=0.005
Boundary for River Rch & Prof#=Sweetwater Creek,Reach-1,7
Up Type=0
Dn Type=3
Dn Slope=0.005

--- Sweetwater Creek Trib 24.g01 (geometry) ---

Geom Title=Existing Conditions

River Reach=Sweetwater Creek,Reach-1
Reach XY= 30
      1390905.00      6846788.00      1390858.39      6846839.41
      1390849.49      6846940.43      1390765.80      6847028.33
      1390746.82      6847094.04      1390658.55      6847189.47
      1390657.06      6847482.15      1390895.21      6847727.48
      1390918.91      6847737.33      1391007.43      6847743.52
      1391141.63      6847874.68      1391154.89      6847906.23
      1391157.27      6848032.06      1391201.22      6848089.57
      1391205.45      6848127.81      1391202.74      6848432.06
      1391158.86      6848489.60      1391151.17      6848586.42
      1391111.12      6848635.82      1391098.92      6848690.20
      1391059.19      6848739.74      1391049.15      6848790.29
      1390965.81      6848878.35      1390949.26      6848940.58
      1390911.47      6848980.30      1390760.03      6848990.18
      1390712.47      6849034.38      1390724.17      6849057.92
      1390897.24      6849231.79      1390905.00      6849288.00

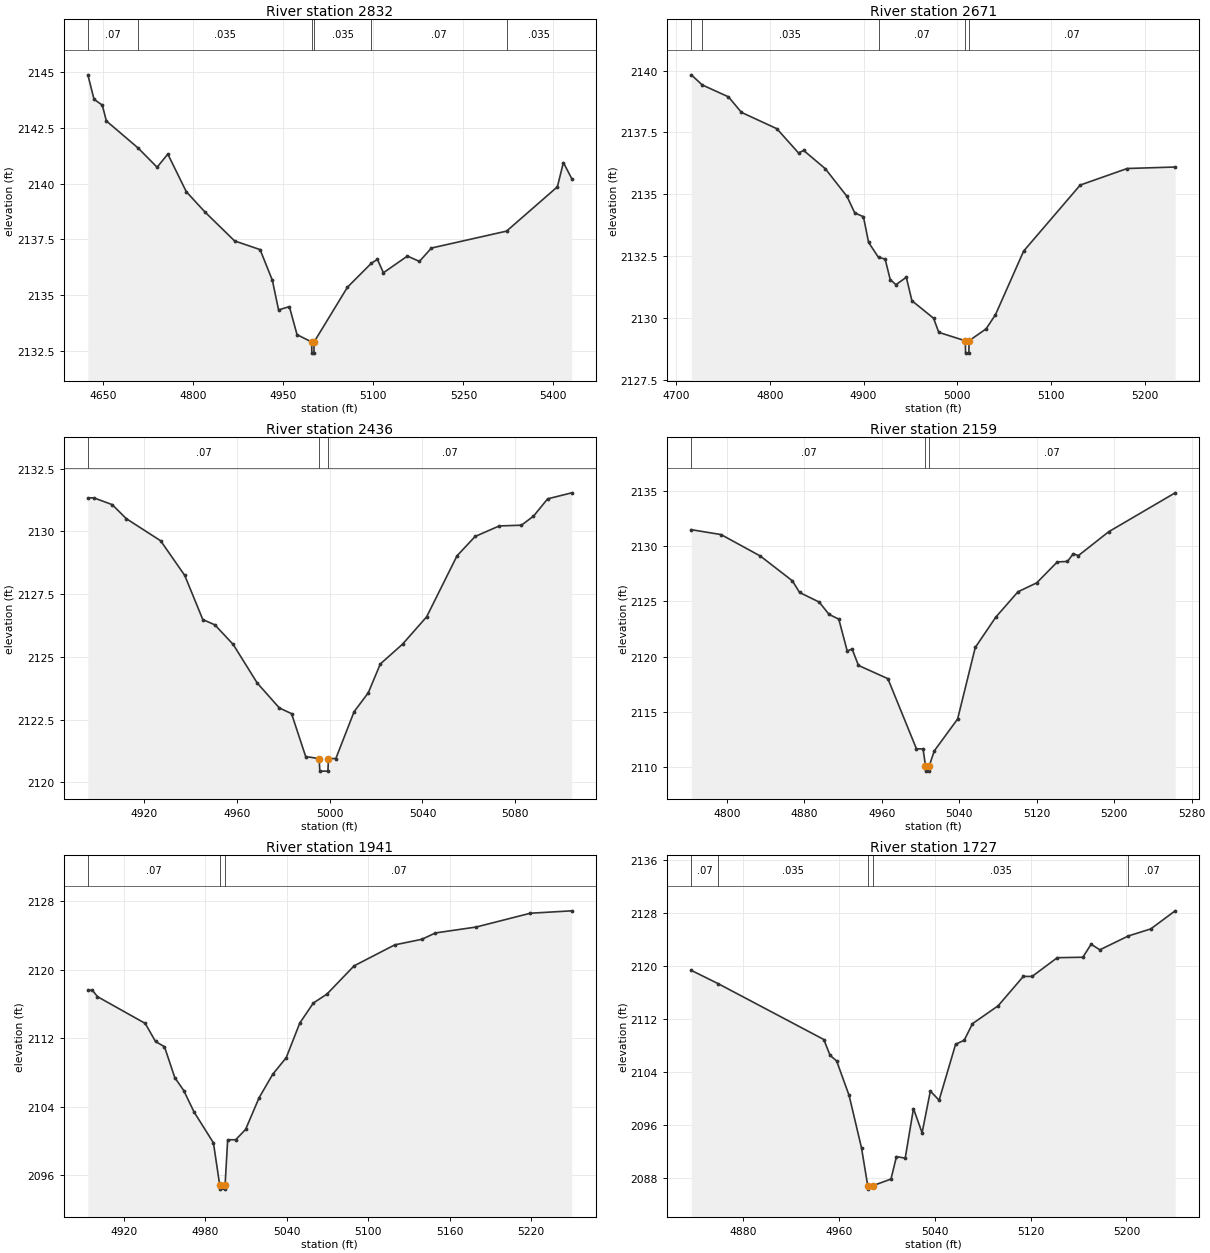
Type RM Length L Ch R = 1,2832,161,161,161
BEGIN DESCRIPTION:
Sweetwater Creek Trib 24 4.0
END DESCRIPTION:
XS GIS Cut Line= 3
      1390655.00      6846738.00      1390738.31      6847104.66
      1391168.91      6847103.47
#Sta/Elev= 30
  4624.0 2144.89  4634.3 2143.79  4648.1 2143.53  4654.8 2142.82  4707.9 2141.60
  4739.4 2140.74  4757.3 2141.33  4788.1 2139.64  4818.8 2138.74  4868.6 2137.43
  4911.1 2137.04  4931.6 2135.66  4941.9 2134.33  4959.9 2134.48  4972.7 2133.22
  4997.1 2132.89  4997.4 2132.39  5000.9 2132.39  5001.1 2132.89  5056.7 2135.35
  5096.7 2136.43  5106.7 2136.60  5116.7 2136.00  5156.7 2136.75  5176.7 2136.51
  5196.7 2137.11  5322.0 2137.87  5406.7 2139.86  5416.7 2140.95  5430.6 2140.23
#Mann=6,-1,0
  4624.0    0.07       0  4707.9   0.035       0  4997.1   0.035       0
  5001.1   0.035       0  5096.7    0.07       0  5322.0   0.035       0
Bank Sta=4997.1,5001.1
Exp/Cntr=0.3,0.1

Type RM Length L Ch R = 1,2671,235,235,235
BEGIN DESCRIPTION:
Sweetwater Creek Trib 24 4498
END DESCRIPTION:
XS GIS Cut Line= 3
      1390396.27      6847115.60      1390654.52      6847232.80
      1390885.86      6847252.77
#Sta/Elev= 30
  4716.4 2139.83  4728.1 2139.42  4756.0 2138.94  4769.9 2138.31  4807.6 2137.65
  4830.7 2136.67  4836.2 2136.77  4859.3 2136.03  4882.4 2134.91  4890.7 2134.24
  4899.9 2134.09  4905.4 2133.05  4916.0 2132.44  4923.0 2132.38  4928.5 2131.54
  4934.6 2131.34  4945.6 2131.64  4951.6 2130.69  4974.7 2129.98  4980.2 2129.41
  5008.5 2129.07  5008.8 2128.57  5012.3 2128.57  5012.5 2129.07  5030.6 2129.55
  5040.6 2130.12  5070.7 2132.70  5131.0 2135.37  5181.1 2136.04  5232.2 2136.10
#Mann=5,-1,0
  4716.4    0.07       0  4728.1   0.035       0  4916.0    0.07       0
  5008.5    0.07       0  5012.5    0.07       0
Bank Sta=5008.5,5012.5
Exp/Cntr=0.3,0.1

Type RM Length L Ch R = 1,2436,277,277,277
BEGIN DESCRIPTION:
Sweetwater Creek Trib 24 3.0
END DESCRIPTION:
XS GIS Cut Line= 3
      1390554.97      6847437.99      1390654.96      6847468.02
      1390754.95      6847438.01
#Sta/Elev= 30
  4895.6 2131.34  4898.2 2131.34  4906.1 2131.07  4912.2 2130.51  4927.0 2129.63
  4937.4 2128.25  4945.2 2126.49  4950.4 2126.28  4958.3 2125.50  4968.7 2123.96
  4978.2 2122.97  4983.5 2122.74  4989.6 2121.03  4995.4 2120.95  4995.7 2120.45
  4999.2 2120.45  4999.4 2120.95  5002.6 2120.95  5010.5 2122.82  5016.6 2123.57
  5021.8 2124.72  5031.4 2125.51  5041.8 2126.60  5054.9 2129.03  5062.7 2129.80
  5073.1 2130.22  5082.7 2130.25  5087.9 2130.61  5094.0 2131.30  5104.4 2131.54
#Mann=3,-1,0
  4895.6    0.07       0  4995.4    0.07       0  4999.4    0.07       0
Bank Sta=4995.4,4999.4
Exp/Cntr=0.3,0.1

Type RM Length L Ch R = 1,2159,218,218,218
BEGIN DESCRIPTION:
Sweetwater Creek Trib 24 4499
END DESCRIPTION:
XS GIS Cut Line= 3
      1390604.65      6847709.37      1390838.29      6847671.43
      1390924.09      6847422.93
#Sta/Elev= 30
  4763.3 2131.46  4794.0 2131.02  4834.6 2129.08  4867.7 2126.84  4875.1 2125.79
  4895.4 2124.92  4905.5 2123.81  4915.6 2123.38  4924.3 2120.50  4929.3 2120.69
  4935.9 2119.20  4966.3 2118.00  4995.8 2111.66  5002.6 2111.66  5005.1 2110.15
  5005.3 2109.65  5008.8 2109.65  5009.1 2110.15  5014.2 2111.48  5038.3 2114.36
  5056.5 2120.82  5077.7 2123.56  5100.6 2125.85  5120.0 2126.66  5141.2 2128.55
  5151.7 2128.59  5157.7 2129.29  5163.0 2129.12  5194.2 2131.27  5262.9 2134.79
#Mann=3,-1,0
  4763.3    0.07       0  5005.1    0.07       0  5009.1    0.07       0
Bank Sta=5005.1,5009.1
Exp/Cntr=0.3,0.1

Type RM Length L Ch R = 1,1941,214,214,214
BEGIN DESCRIPTION:
Sweetwater Creek Trib 24 2.0
END DESCRIPTION:
XS GIS Cut Line= 3
      1390954.99      6847838.01      1391025.16      6847757.63
      1391027.27      6847507.53
#Sta/Elev= 30
  4893.3 2117.61  4896.6 2117.61  4900.4 2116.86  4935.6 2113.74  4943.2 2111.63
  4949.8 2111.02  4957.4 2107.42  4964.0 2105.91  4971.6 2103.41  4985.9 2099.81
  4990.5 2094.91  4990.8 2094.41  4994.3 2094.41  4994.5 2094.91  4996.4 2100.17
  5002.3 2100.17  5009.6 2101.37  5019.6 2105.08  5029.6 2107.80  5039.6 2109.75
  5049.6 2113.79  5059.6 2116.12  5069.6 2117.16  5089.6 2120.45  5119.6 2122.90
  5139.6 2123.55  5149.6 2124.29  5179.6 2124.98  5219.6 2126.59  5250.1 2126.87
#Mann=3,-1,0
  4893.3    0.07       0  4990.5    0.07       0  4994.5    0.07       0
Bank Sta=4990.5,4994.5
Exp/Cntr=0.3,0.1

Type RM Length L Ch R = 1,1727,284,284,284
BEGIN DESCRIPTION:
Sweetwater Creek Trib 24 4493
END DESCRIPTION:
XS GIS Cut Line= 3
      1390998.42      6847965.26      1391155.43      6847919.64
      1391320.91      6847744.85
#Sta/Elev= 30
  4836.5 2119.33  4859.2 2117.30  4947.2 2108.90  4952.4 2106.52  4957.9 2105.67
  4968.3 2100.48  4978.7 2092.54  4983.9 2086.83  4984.2 2086.33  4987.9 2086.83
  5003.3 2087.85  5007.9 2091.24  5015.2 2091.00  5022.1 2098.48  5029.3 2094.82
  5036.2 2101.12  5043.5 2099.74  5057.3 2108.18  5064.5 2108.79  5071.4 2111.29
  5092.8 2113.98  5113.9 2118.42  5121.2 2118.41  5142.2 2121.24  5163.6 2121.31
  5170.5 2123.27  5177.8 2122.43  5201.6 2124.52  5220.3 2125.58  5240.7 2128.31
#Mann=5,-1,0
  4836.5    0.07       0  4859.2   0.035       0  4983.9   0.035       0
  4987.9   0.035       0  5201.6    0.07       0
Bank Sta=4983.9,4987.9
Exp/Cntr=0.3,0.1

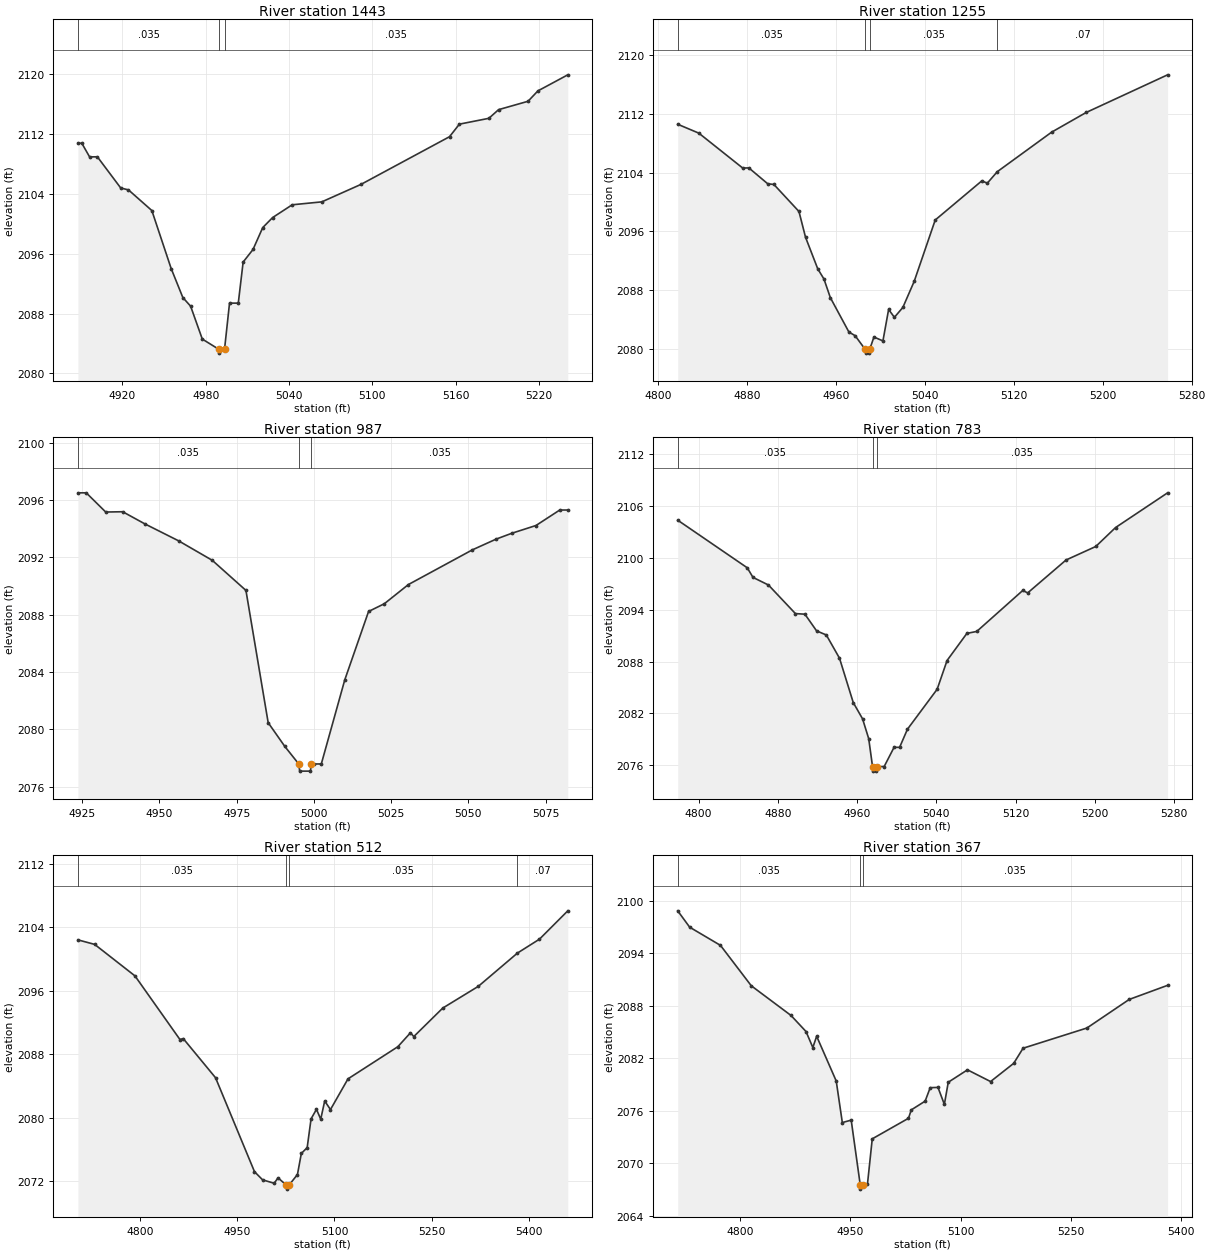
Type RM Length L Ch R = 1,1443,188,188,188
BEGIN DESCRIPTION:
Sweetwater Creek Trib 24 1.0
END DESCRIPTION:
XS GIS Cut Line= 3
      1391104.96      6848137.98      1391205.08      6848187.97
      1391375.56      6848018.19
#Sta/Elev= 30
  4888.1 2110.80  4890.9 2110.80  4896.5 2108.97  4902.1 2108.98  4918.9 2104.81
  4924.5 2104.55  4941.3 2101.79  4955.2 2094.03  4963.6 2090.15  4969.2 2088.99
  4977.6 2084.59  4989.6 2083.21  4989.9 2082.71  4993.6 2083.21  4997.2 2089.40
  5003.5 2089.40  5007.0 2094.90  5014.1 2096.58  5021.1 2099.51  5028.2 2100.85
  5042.3 2102.56  5063.6 2102.95  5091.8 2105.29  5155.5 2111.67  5162.6 2113.35
  5183.8 2114.13  5190.8 2115.29  5212.0 2116.41  5219.1 2117.80  5240.6 2119.95
#Mann=3,-1,0
  4888.1   0.035       0  4989.6   0.035       0  4993.6   0.035       0
Bank Sta=4989.6,4993.6
Exp/Cntr=0.3,0.1

Type RM Length L Ch R = 1,1255,268,268,268
BEGIN DESCRIPTION:
Sweetwater Creek Trib 24 4492
END DESCRIPTION:
XS GIS Cut Line= 3
      1391041.87      6848295.11      1391205.31      6848375.40
      1391456.36      6848314.64
#Sta/Elev= 30
  4817.9 2110.58  4836.9 2109.37  4876.3 2104.63  4881.9 2104.64  4898.8 2102.49
  4904.4 2102.39  4926.9 2098.72  4932.8 2095.22  4943.8 2090.92  4949.4 2089.53
  4955.1 2087.01  4971.8 2082.33  4977.4 2081.83  4986.5 2079.96  4986.8 2079.46
  4990.3 2079.46  4990.5 2079.96  4994.3 2081.65  5002.4 2081.12  5007.5 2085.40
  5012.7 2084.33  5020.3 2085.67  5030.5 2089.22  5049.4 2097.56  5091.2 2102.87
  5096.3 2102.58  5105.2 2104.13  5154.0 2109.50  5185.1 2112.18  5258.3 2117.30
#Mann=4,-1,0
  4817.9   0.035       0  4986.5   0.035       0  4990.5   0.035       0
  5105.2    0.07       0
Bank Sta=4986.5,4990.5
Exp/Cntr=0.3,0.1

Type RM Length L Ch R = 1,987,204,204,204
BEGIN DESCRIPTION:
Sweetwater Creek Trib 24 465
END DESCRIPTION:
XS GIS Cut Line= 3
      1391055.04      6848588.02      1391125.27      6848618.11
      1391205.02      6848638.01
#Sta/Elev= 26
  4923.6 2096.50  4926.3 2096.50  4932.6 2095.16  4938.1 2095.18  4945.3 2094.33
  4956.2 2093.15  4967.1 2091.79  4978.0 2089.69  4985.2 2080.46  4990.6 2078.80
  4995.1 2077.58  4995.4 2077.08  4998.9 2077.08  4999.1 2077.58  5000.0 2077.58
  5002.4 2077.58  5010.0 2083.45  5017.7 2088.22  5022.8 2088.76  5030.6 2090.10
  5051.3 2092.52  5059.0 2093.27  5064.1 2093.68  5071.9 2094.22  5079.6 2095.30
  5082.2 2095.30
#Mann=3,-1,0
  4923.6   0.035       0  4995.1   0.035       0  4999.1   0.035       0
Bank Sta=4995.1,4999.1
Exp/Cntr=0.3,0.1

Type RM Length L Ch R = 1,783,271,271,271
BEGIN DESCRIPTION:
Sweetwater Creek Trib 24 4494
END DESCRIPTION:
XS GIS Cut Line= 3
      1390931.20      6848607.64      1391044.21      6848797.67
      1391317.43      6848787.74
#Sta/Elev= 30
  4778.9 2104.33  4849.1 2098.83  4854.9 2097.72  4870.5 2096.84  4897.7 2093.54
  4907.3 2093.47  4919.1 2091.54  4928.9 2091.07  4942.2 2088.39  4956.1 2083.26
  4965.5 2081.38  4971.7 2079.09  4975.6 2075.84  4975.8 2075.34  4979.3 2075.34
  4979.6 2075.84  4987.3 2075.87  4997.3 2078.09  5002.9 2078.09  5010.8 2080.18
  5040.8 2084.80  5050.8 2088.12  5070.8 2091.25  5080.8 2091.48  5127.2 2096.21
  5132.2 2095.93  5170.9 2099.73  5200.9 2101.29  5220.9 2103.48  5273.4 2107.49
#Mann=3,-1,0
  4778.9   0.035       0  4975.6   0.035       0  4979.6   0.035       0
Bank Sta=4975.6,4979.6
Exp/Cntr=0.3,0.1

Type RM Length L Ch R = 1,512,145,145,145
BEGIN DESCRIPTION:
Sweetwater Creek Trib 24 4495
END DESCRIPTION:
XS GIS Cut Line= 4
      1390798.81      6848703.09      1390875.23      6848988.43
      1391004.97      6849076.36      1391301.18      6849013.66
#Sta/Elev= 30
  4704.6 2102.42  4730.4 2101.85  4792.5 2097.88  4861.8 2089.86  4867.0 2089.97
  4916.7 2085.04  4976.7 2073.20  4989.2 2072.17  5007.0 2071.74  5013.0 2072.42
  5025.9 2071.50  5026.2 2071.00  5029.9 2071.50  5042.9 2072.84  5048.9 2075.50
  5057.9 2076.23  5063.9 2079.86  5072.2 2081.06  5078.8 2079.82  5084.9 2082.11
  5093.8 2081.03  5120.8 2084.90  5197.6 2088.95  5217.1 2090.71  5222.2 2090.23
  5266.8 2093.82  5321.6 2096.56  5382.0 2100.76  5415.9 2102.51  5459.5 2106.08
#Mann=4,-1,0
  4704.6   0.035       0  5025.9   0.035       0  5029.9   0.035       0
  5382.0    0.07       0
Bank Sta=5025.9,5029.9
Exp/Cntr=0.3,0.1

Type RM Length L Ch R = 1,367,0,0,0
BEGIN DESCRIPTION:
Sweetwater Creek Trib 24 4496
END DESCRIPTION:
XS GIS Cut Line= 4
      1390744.00      6848747.90      1390690.84      6848969.21
      1390761.37      6849027.81      1391091.67      6849138.98
#Sta/Elev= 30
  4714.5 2098.84  4730.8 2096.97  4772.8 2094.89  4814.8 2090.27  4868.9 2086.88
  4889.4 2085.04  4898.7 2083.21  4903.9 2084.50  4930.6 2079.38  4938.9 2074.63
  4951.0 2074.91  4963.3 2067.52  4963.6 2067.02  4967.3 2067.52  4973.2 2067.61
  4979.7 2072.77  5029.1 2075.12  5032.9 2076.08  5051.8 2077.08  5058.7 2078.62
  5069.3 2078.65  5078.0 2076.71  5083.3 2079.24  5109.5 2080.66  5141.0 2079.32
  5172.5 2081.40  5185.3 2083.13  5272.3 2085.44  5330.0 2088.71  5382.3 2090.32
#Mann=3,-1,0
  4714.5   0.035       0  4963.3   0.035       0  4967.3   0.035       0
Bank Sta=4963.3,4967.3
Exp/Cntr=0.3,0.1

Chan Stop Cuts=-1