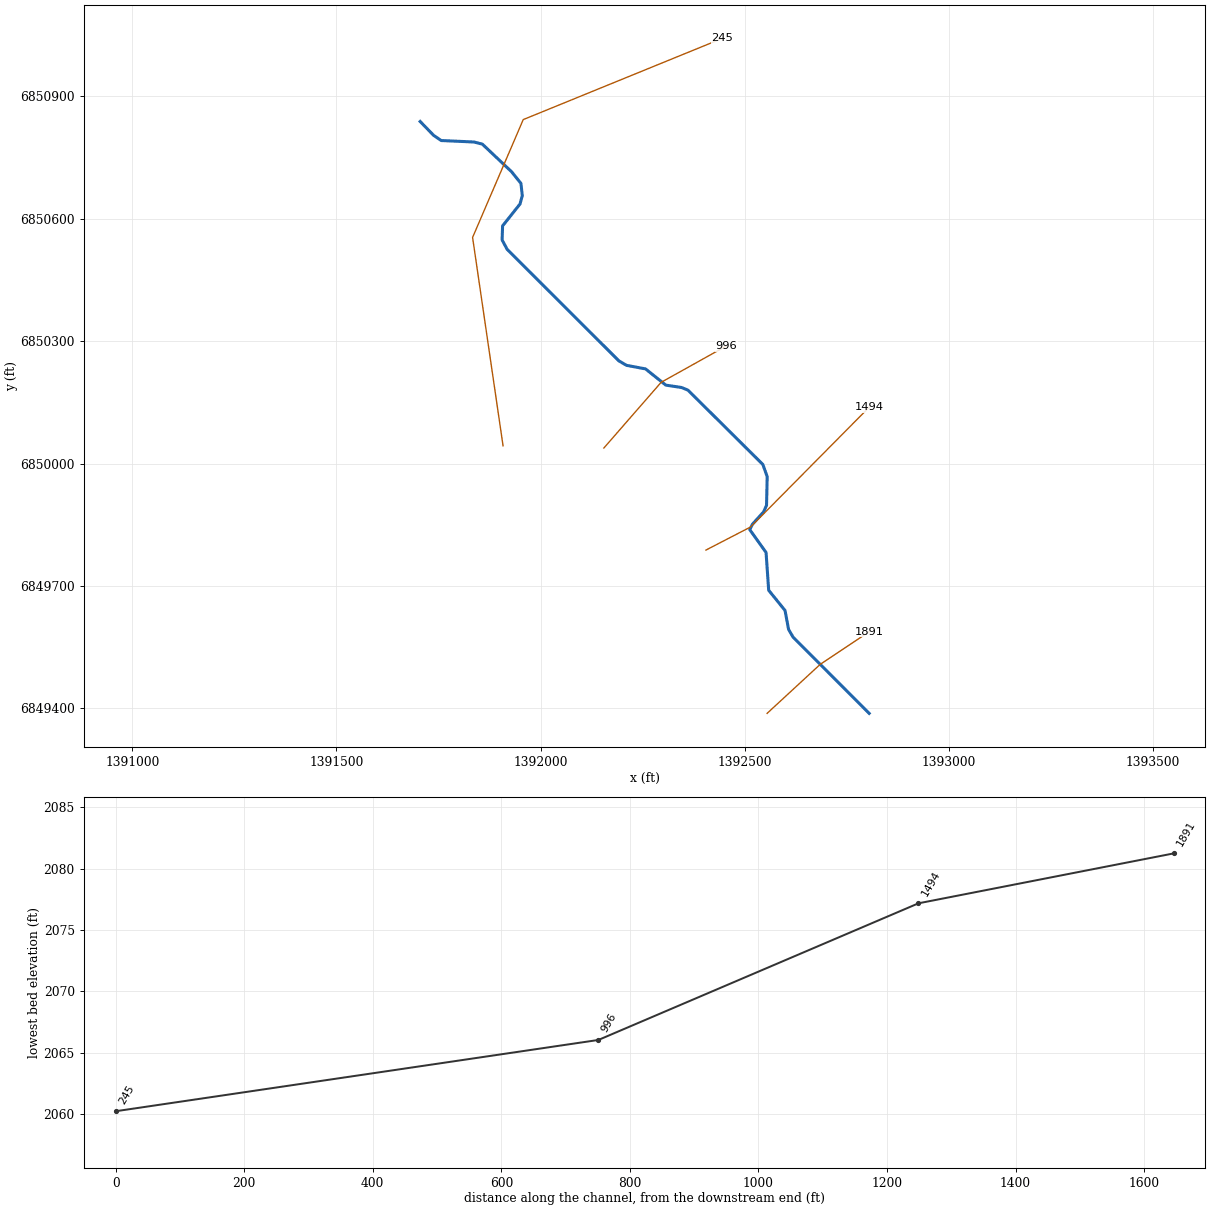
--- Sweetwater Creek Trib 25.prj (project) ---

Proj Title=Sweetwater Creek Trib 25 Base Level Engineering
Current Plan=p01
Default Exp/Contr=0.3,0.1
English Units
Geom File=g01
Flow File=f01
Plan File=p01
BEGIN DESCRIPTION:
Sweetwater Creek Trib 25
END DESCRIPTION:

--- Sweetwater Creek Trib 25.p01 (plan) ---

Plan Title=Multiple Run
Short Identifier=Multiple
Geom File=g01
Flow File=f01
Subcritical Flow
K Sum by GR= 0
Std Step Tol= 0.01
Critical Tol= 0.01
Num of Std Step Trials= 20
Max Error Tol= 0.3
Flow Tol Ratio= 0.001
Split Flow NTrial= 30
Split Flow Tol= 0.02
Split Flow Ratio= 0.02
Log Output Level= 0
Friction Slope Method= 1
Unsteady Friction Slope Method= 2
Unsteady Bridges Friction Slope Method= 1
Parabolic Critical Depth
Global Vel Dist=  1 , 1 , 1
Global Log Level= 0
CheckData=True
Encroach Param= -1, 0, 0, 0
BEGIN DESCRIPTION:
Multiple Run
END DESCRIPTION:

--- Sweetwater Creek Trib 25.f01 (steady flow) ---

Flow Title=Multiple
Number of Profiles=7
Profile Names=10-year,25-year,50-year,1pct_min,100-year,1pct_plu,500-year
River Rch & RM= Sweetwater Creek,Reach-1,1891
     337     486     614     386     771    1538    1230
River Rch & RM= Sweetwater Creek,Reach-1,996
     331     481     609     384     767    1530    1231
Boundary for River Rch & Prof#=Sweetwater Creek,Reach-1,1
Up Type=0
Dn Type=3
Dn Slope=0.005
Boundary for River Rch & Prof#=Sweetwater Creek,Reach-1,2
Up Type=0
Dn Type=3
Dn Slope=0.005
Boundary for River Rch & Prof#=Sweetwater Creek,Reach-1,3
Up Type=0
Dn Type=3
Dn Slope=0.005
Boundary for River Rch & Prof#=Sweetwater Creek,Reach-1,4
Up Type=0
Dn Type=3
Dn Slope=0.005
Boundary for River Rch & Prof#=Sweetwater Creek,Reach-1,5
Up Type=0
Dn Type=3
Dn Slope=0.005
Boundary for River Rch & Prof#=Sweetwater Creek,Reach-1,6
Up Type=0
Dn Type=3
Dn Slope=0.005
Boundary for River Rch & Prof#=Sweetwater Creek,Reach-1,7
Up Type=0
Dn Type=3
Dn Slope=0.005

--- Sweetwater Creek Trib 25.g01 (geometry) ---

Geom Title=Existing Conditions

River Reach=Sweetwater Creek,Reach-1
Reach XY= 30
      1392805.00      6849388.00      1392618.62      6849574.78
      1392607.61      6849593.62      1392598.86      6849640.17
      1392558.82      6849689.59      1392552.45      6849782.11
      1392512.56      6849838.00      1392518.96      6849851.21
      1392546.60      6849881.84      1392553.57      6849897.64
      1392555.20      6849967.94      1392544.56      6849997.79
      1392361.06      6850179.86      1392345.22      6850186.34
      1392306.74      6850192.19      1392257.19      6850231.90
      1392210.63      6850240.61      1392191.79      6850251.62
      1391918.12      6850524.79      1391905.76      6850547.78
      1391906.93      6850582.28      1391949.61      6850635.81
      1391955.24      6850656.46      1391951.87      6850686.38
      1391928.99      6850714.89      1391857.45      6850782.51
      1391836.75      6850787.81      1391756.41      6850791.39
      1391737.95      6850804.13      1391705.00      6850838.00

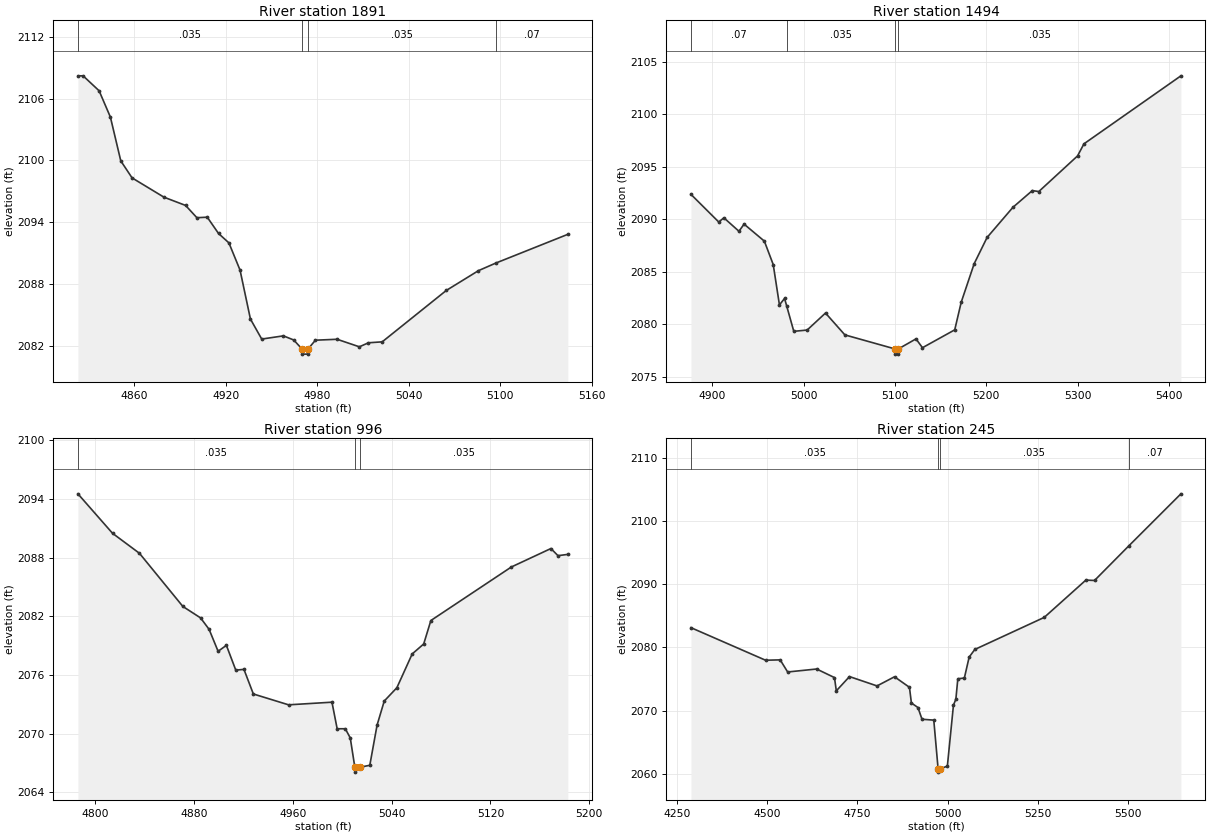
Type RM Length L Ch R = 1,1891,397,397,397
BEGIN DESCRIPTION:
Sweetwater Creek Trib 25 2.0
END DESCRIPTION:
XS GIS Cut Line= 3
      1392554.98      6849387.98      1392684.96      6849507.98
      1392805.03      6849588.02
#Sta/Elev= 30
  4823.1 2108.20  4826.5 2108.20  4837.0 2106.75  4844.4 2104.20  4851.2 2099.96
  4858.6 2098.31  4879.5 2096.44  4893.7 2095.64  4901.1 2094.45  4907.9 2094.50
  4915.3 2092.92  4922.1 2092.01  4929.4 2089.37  4936.2 2084.63  4943.6 2082.69
  4957.8 2083.00  4964.6 2082.60  4970.0 2081.73  4970.2 2081.23  4973.7 2081.23
  4974.0 2081.73  4978.8 2082.58  4993.0 2082.67  5007.6 2081.94  5013.6 2082.33
  5022.6 2082.42  5064.6 2087.40  5085.7 2089.32  5097.0 2090.05  5144.3 2092.84
#Mann=4,-1,0
  4823.1   0.035       0  4970.0   0.035       0  4974.0   0.035       0
  5097.0    0.07       0
Bank Sta=4970,4974
Exp/Cntr=0.3,0.1

Type RM Length L Ch R = 1,1494,498,498,498
BEGIN DESCRIPTION:
Sweetwater Creek Trib 25 1.0
END DESCRIPTION:
XS GIS Cut Line= 3
      1392405.03      6849788.01      1392514.46      6849844.60
      1392804.99      6850137.99
#Sta/Elev= 30
  4876.8 2092.37  4907.2 2089.74  4912.8 2090.14  4929.3 2088.86  4934.9 2089.54
  4957.1 2087.92  4966.8 2085.69  4973.6 2081.85  4979.2 2082.47  4981.4 2081.79
  4989.3 2079.34  5003.9 2079.46  5024.0 2081.08  5045.2 2079.00  5099.8 2077.67
  5100.1 2077.17  5103.6 2077.17  5103.8 2077.67  5123.0 2078.62  5130.1 2077.78
  5165.4 2079.48  5172.5 2082.11  5186.7 2085.78  5200.8 2088.27  5229.1 2091.14
  5250.3 2092.73  5257.4 2092.64  5299.8 2096.03  5306.8 2097.18  5412.9 2103.65
#Mann=4,-1,0
  4876.8    0.07       0  4981.4   0.035       0  5099.8   0.035       0
  5103.8   0.035       0
Bank Sta=5099.8,5103.8
Exp/Cntr=0.3,0.1

Type RM Length L Ch R = 1,996,751,751,751
BEGIN DESCRIPTION:
Sweetwater Creek Trib 25 462
END DESCRIPTION:
XS GIS Cut Line= 3
      1392155.02      6850038.02      1392295.45      6850199.10
      1392454.96      6850287.98
#Sta/Elev= 30
  4786.3 2094.54  4814.3 2090.50  4836.1 2088.45  4871.2 2083.01  4885.5 2081.84
  4892.4 2080.67  4899.7 2078.42  4906.4 2079.03  4914.0 2076.49  4920.6 2076.57
  4928.2 2074.05  4956.7 2072.94  4991.8 2073.21  4996.0 2070.49  5002.6 2070.49
  5006.6 2069.55  5010.3 2066.55  5010.6 2066.05  5014.3 2066.55  5022.4 2066.75
  5028.3 2070.87  5034.1 2073.33  5044.3 2074.69  5056.7 2078.15  5066.0 2079.17
  5071.8 2081.57  5136.9 2087.05  5168.9 2088.94  5174.6 2088.21  5182.6 2088.34
#Mann=3,-1,0
  4786.3   0.035       0  5010.3   0.035       0  5014.3   0.035       0
Bank Sta=5010.3,5014.3
Exp/Cntr=0.3,0.1

Type RM Length L Ch R = 1,245,0,0,0
BEGIN DESCRIPTION:
Sweetwater Creek Trib 25 3913
END DESCRIPTION:
XS GIS Cut Line= 4
      1391908.07      6850043.52      1391833.45      6850553.96
      1391957.52      6850842.66      1392445.58      6851041.76
#Sta/Elev= 30
  4289.0 2083.14  4495.7 2077.98  4536.1 2078.04  4556.8 2076.12  4637.1 2076.59
  4686.5 2075.23  4691.6 2073.13  4728.1 2075.39  4804.4 2073.91  4852.8 2075.36
  4894.2 2073.69  4899.6 2071.20  4917.7 2070.49  4929.0 2068.63  4961.6 2068.49
  4973.6 2060.75  4973.9 2060.25  4977.7 2060.75  4999.2 2061.20  5016.1 2070.86
  5022.8 2071.82  5028.2 2075.04  5046.3 2075.16  5059.6 2078.48  5075.3 2079.69
  5267.6 2084.77  5382.9 2090.68  5406.9 2090.62  5501.1 2096.06  5646.2 2104.35
#Mann=4,-1,0
  4289.0   0.035       0  4973.6   0.035       0  4977.7   0.035       0
  5501.1    0.07       0
Bank Sta=4973.6,4977.7
Exp/Cntr=0.3,0.1

Chan Stop Cuts=-1