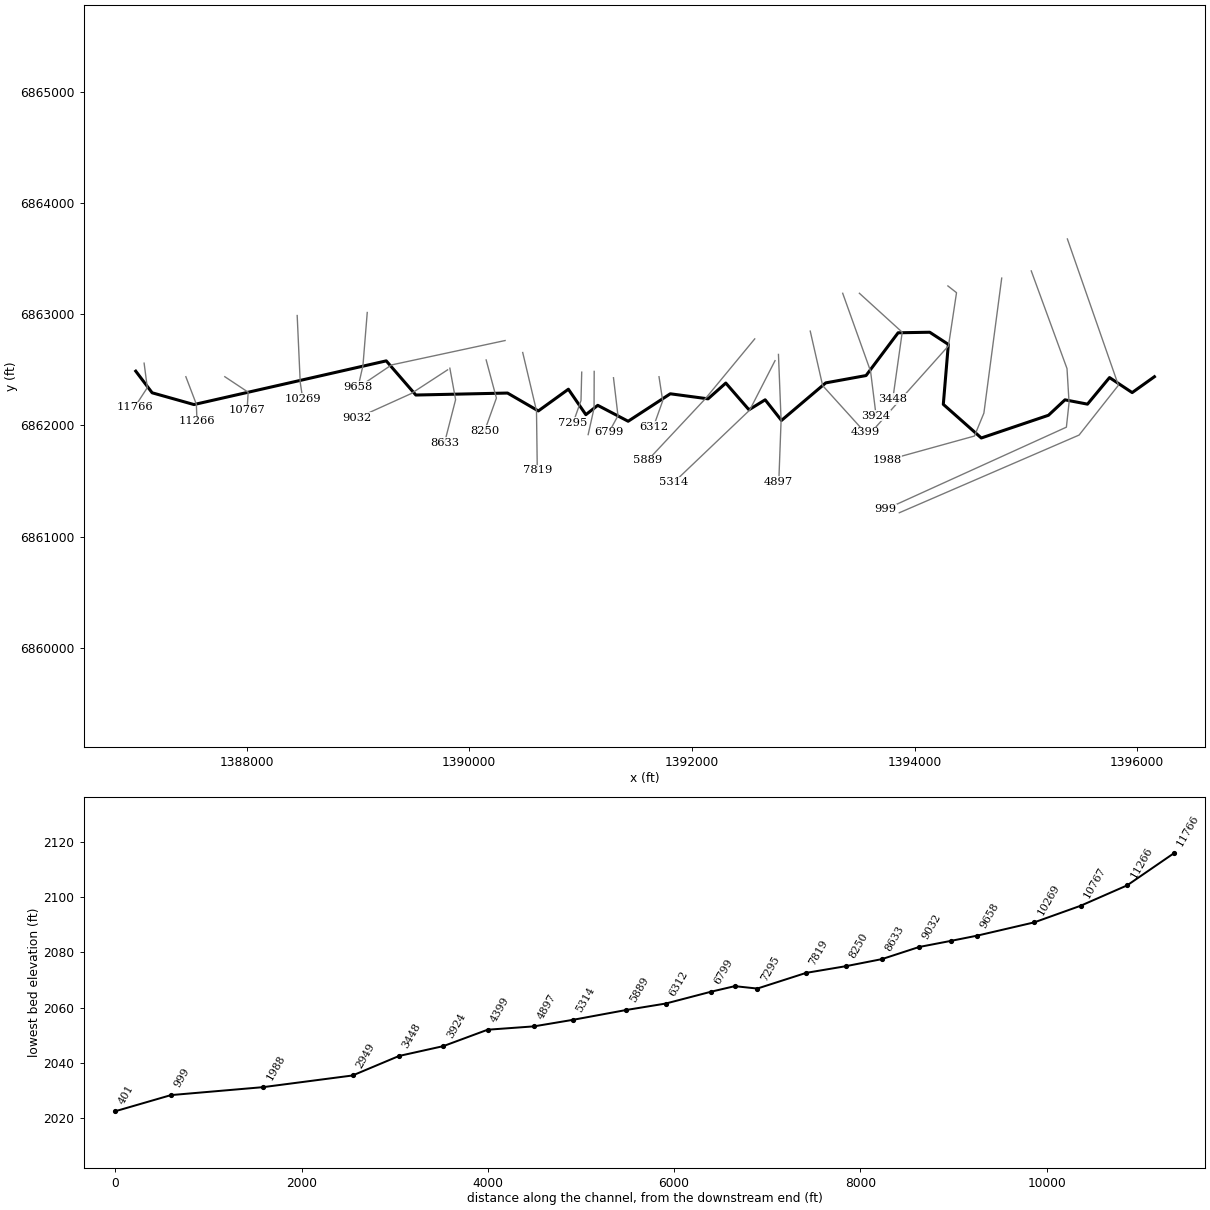
--- Sweetwater Creek Trib 26.prj (project) ---

Proj Title=Sweetwater Creek Trib 26 Base Level Engineering
Current Plan=p01
Default Exp/Contr=0.3,0.1
English Units
Geom File=g01
Flow File=f01
Plan File=p01
BEGIN DESCRIPTION:
Sweetwater Creek Trib 26
END DESCRIPTION:

--- Sweetwater Creek Trib 26.p01 (plan) ---

Plan Title=Multiple Run
Short Identifier=Multiple
Geom File=g01
Flow File=f01
Subcritical Flow
K Sum by GR= 0
Std Step Tol= 0.01
Critical Tol= 0.01
Num of Std Step Trials= 20
Max Error Tol= 0.3
Flow Tol Ratio= 0.001
Split Flow NTrial= 30
Split Flow Tol= 0.02
Split Flow Ratio= 0.02
Log Output Level= 0
Friction Slope Method= 1
Unsteady Friction Slope Method= 2
Unsteady Bridges Friction Slope Method= 1
Parabolic Critical Depth
Global Vel Dist=  1 , 1 , 1
Global Log Level= 0
CheckData=True
Encroach Param= -1, 0, 0, 0
BEGIN DESCRIPTION:
Multiple Run
END DESCRIPTION:

--- Sweetwater Creek Trib 26.f01 (steady flow) ---

Flow Title=Multiple
Number of Profiles=7
Profile Names=10-year,25-year,50-year,1pct_min,100-year,1pct_plu,500-year
River Rch & RM= Sweetwater Creek,Reach-1,11766
     285     406     508     316     631    1259     986
River Rch & RM= Sweetwater Creek,Reach-1,4399
     330     469     586     363     725    1447    1126
Boundary for River Rch & Prof#=Sweetwater Creek,Reach-1,1
Up Type=0
Dn Type=3
Dn Slope=0.005
Boundary for River Rch & Prof#=Sweetwater Creek,Reach-1,2
Up Type=0
Dn Type=3
Dn Slope=0.005
Boundary for River Rch & Prof#=Sweetwater Creek,Reach-1,3
Up Type=0
Dn Type=3
Dn Slope=0.005
Boundary for River Rch & Prof#=Sweetwater Creek,Reach-1,4
Up Type=0
Dn Type=3
Dn Slope=0.005
Boundary for River Rch & Prof#=Sweetwater Creek,Reach-1,5
Up Type=0
Dn Type=3
Dn Slope=0.005
Boundary for River Rch & Prof#=Sweetwater Creek,Reach-1,6
Up Type=0
Dn Type=3
Dn Slope=0.005
Boundary for River Rch & Prof#=Sweetwater Creek,Reach-1,7
Up Type=0
Dn Type=3
Dn Slope=0.005

--- Sweetwater Creek Trib 26.g01 (geometry) ---

Geom Title=Existing Conditions

River Reach=Sweetwater Creek,Reach-1
Reach XY= 30
      1387005.00      6862488.00      1387152.33      6862293.42
      1387527.84      6862187.71      1389255.00      6862580.44
      1389520.68      6862273.37      1390344.40      6862291.12
      1390621.14      6862130.34      1390891.01      6862325.53
      1391048.01      6862096.83      1391154.91      6862180.69
      1391427.80      6862037.61      1391806.50      6862284.54
      1392145.41      6862239.20      1392305.00      6862380.93
      1392513.21      6862140.76      1392658.58      6862230.51
      1392804.99      6862045.07      1393202.55      6862382.53
      1393564.81      6862448.51      1393852.71      6862832.89
      1394136.73      6862837.82      1394303.86      6862728.57
      1394258.75      6862189.55      1394599.97      6861887.19
      1395203.54      6862091.54      1395351.58      6862230.20
      1395553.75      6862191.44      1395751.66      6862430.40
      1395955.09      6862295.28      1396155.00      6862438.00

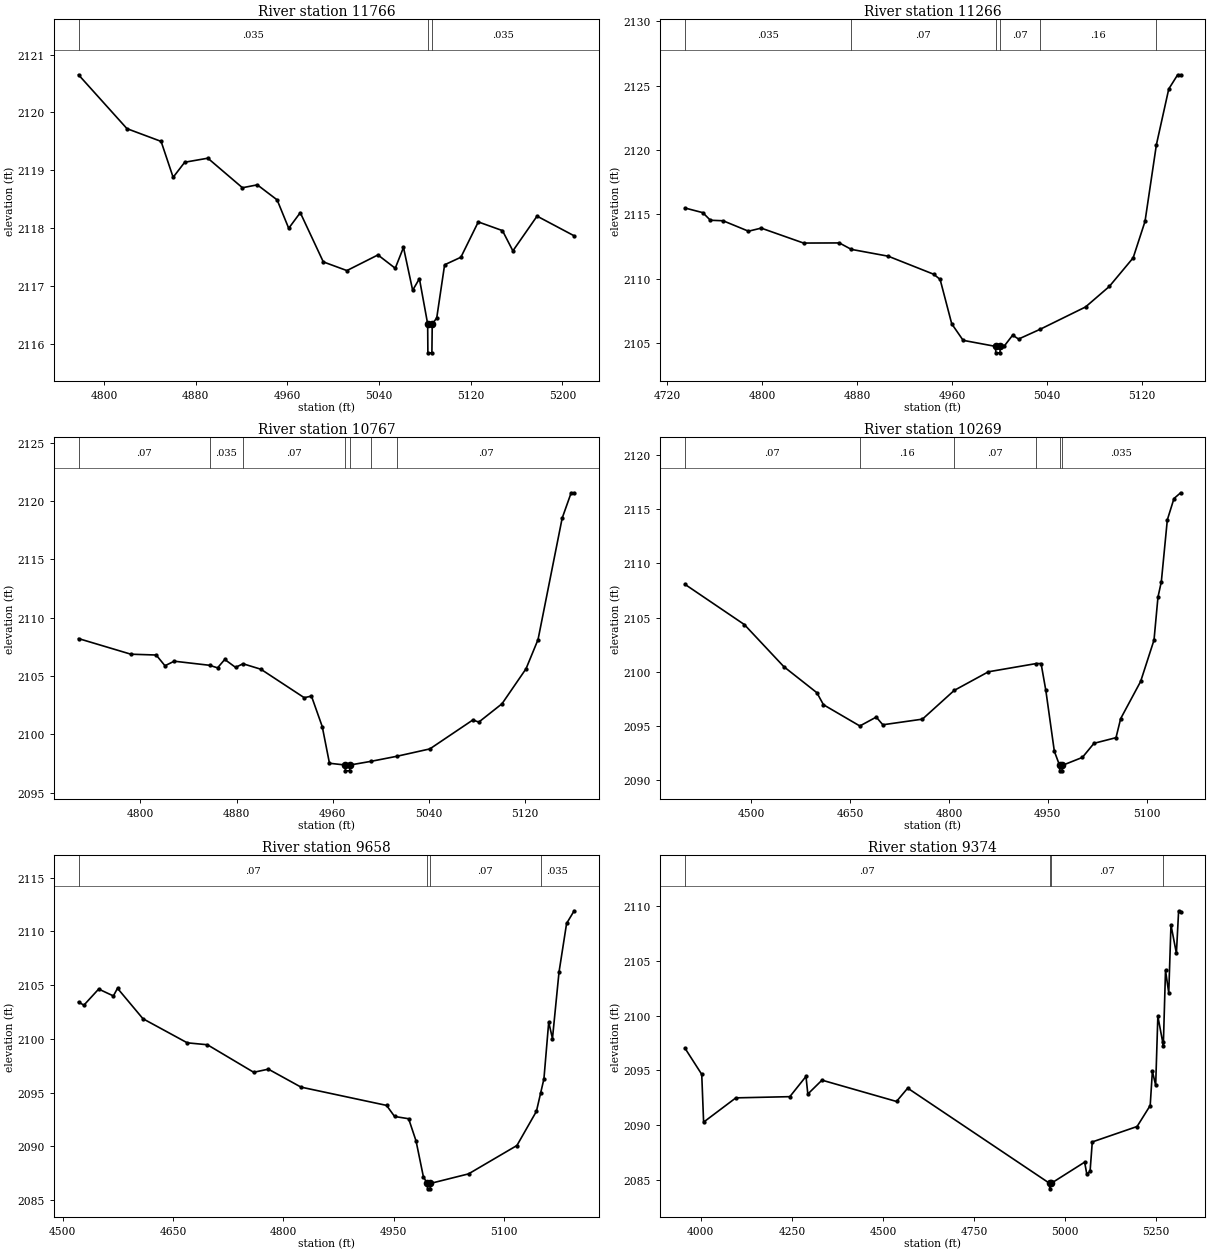
Type RM Length L Ch R = 1,11766,500,500,500
BEGIN DESCRIPTION:
Sweetwater Creek Trib 26 20.0
END DESCRIPTION:
XS GIS Cut Line= 3
      1387080.06      6862559.92      1387108.86      6862339.40
      1386994.06      6862163.20
#Sta/Elev= 30
  4777.6 2120.65  4819.9 2119.72  4849.7 2119.50  4860.2 2118.88  4870.3 2119.14
  4890.5 2119.21  4920.7 2118.70  4933.7 2118.75  4951.0 2118.49  4961.1 2118.00
  4971.2 2118.27  4991.3 2117.42  5011.9 2117.27  5039.0 2117.54  5054.1 2117.31
  5061.3 2117.67  5069.3 2116.93  5075.2 2117.13  5082.4 2116.35  5082.6 2115.85
  5086.1 2115.85  5086.4 2116.35  5090.3 2116.45  5097.2 2117.37  5111.4 2117.50
  5126.6 2118.11  5147.7 2117.96  5156.8 2117.61  5177.9 2118.21  5210.3 2117.87
#Mann=3,-1,0
  4777.6   0.035       0  5082.4   0.035       0  5086.4   0.035       0
Bank Sta=5082.4,5086.4
Exp/Cntr=0.3,0.1

Type RM Length L Ch R = 1,11266,499,499,499
BEGIN DESCRIPTION:
Sweetwater Creek Trib 26 19.0
END DESCRIPTION:
XS GIS Cut Line= 3
      1387455.01      6862437.97      1387549.47      6862190.38
      1387555.00      6862037.98
#Sta/Elev= 30
  4735.0 2115.50  4750.0 2115.14  4756.4 2114.55  4767.1 2114.51  4788.5 2113.70
  4799.2 2113.94  4834.9 2112.78  4865.0 2112.79  4875.1 2112.29  4906.2 2111.76
  4944.5 2110.36  4949.9 2109.96  4959.7 2106.51  4969.3 2105.23  4996.6 2104.76
  4996.8 2104.26  5000.3 2104.26  5000.6 2104.76  5003.7 2104.76  5011.0 2105.63
  5016.0 2105.33  5034.2 2106.09  5072.4 2107.82  5092.4 2109.41  5112.5 2111.63
  5122.5 2114.46  5132.1 2120.42  5142.5 2124.74  5150.0 2125.84  5152.5 2125.84
#Mann=6,-1,0
  4735.0   0.035       0  4875.1    0.07       0  4996.6    0.07       0
  5000.6    0.07       0  5034.2    0.16       0  5132.1   0.035       0
Bank Sta=4996.6,5000.6
Exp/Cntr=0.3,0.1

Type RM Length L Ch R = 1,10767,498,498,498
BEGIN DESCRIPTION:
Sweetwater Creek Trib 26 18.0
END DESCRIPTION:
XS GIS Cut Line= 3
      1387804.99      6862438.01      1388014.63      6862298.89
      1388005.00      6862137.98
#Sta/Elev= 30
  4748.4 2108.22  4792.0 2106.88  4813.1 2106.81  4820.4 2105.89  4828.1 2106.28
  4857.5 2105.93  4864.2 2105.71  4870.2 2106.43  4879.2 2105.75  4885.4 2106.06
  4900.3 2105.59  4936.4 2103.15  4942.4 2103.29  4951.4 2100.67  4957.4 2097.53
  4970.5 2097.38  4970.7 2096.88  4974.2 2096.88  4974.5 2097.38  4992.3 2097.70
  5013.6 2098.13  5041.0 2098.76  5076.8 2101.24  5081.8 2101.06  5101.1 2102.63
  5121.1 2105.63  5131.1 2108.13  5151.2 2118.54  5158.7 2120.72  5161.2 2120.72
#Mann=7,-1,0
  4748.4    0.07       0  4857.5   0.035       0  4885.4    0.07       0
  4970.5   0.035       0  4974.5    0.07       0  4992.3   0.035       0
  5013.6    0.07       0
Bank Sta=4970.5,4974.5
Exp/Cntr=0.3,0.1

Type RM Length L Ch R = 1,10269,611,611,611
BEGIN DESCRIPTION:
Sweetwater Creek Trib 26 17.0
END DESCRIPTION:
XS GIS Cut Line= 3
      1388455.00      6862987.99      1388482.31      6862387.91
      1388505.00      6862238.01
#Sta/Elev= 30
  4399.3 2108.07  4489.4 2104.36  4549.4 2100.47  4599.5 2098.07  4609.5 2096.96
  4664.7 2095.00  4689.6 2095.82  4699.6 2095.11  4759.7 2095.63  4807.9 2098.28
  4859.8 2100.00  4932.4 2100.76  4939.8 2100.76  4947.0 2098.28  4959.9 2092.67
  4967.9 2091.36  4968.1 2090.86  4971.6 2090.86  4971.9 2091.36  5002.5 2092.10
  5020.1 2093.40  5053.5 2093.92  5060.6 2095.68  5090.9 2099.11  5111.2 2102.93
  5117.2 2106.89  5122.3 2108.31  5131.4 2114.02  5141.5 2115.99  5151.6 2116.52
#Mann=6,-1,0
  4399.3    0.07       0  4664.7    0.16       0  4807.9    0.07       0
  4932.4   0.035       0  4967.9   0.035       0  4971.9   0.035       0
Bank Sta=4967.9,4971.9
Exp/Cntr=0.3,0.1

Type RM Length L Ch R = 1,9658,284,284,284
BEGIN DESCRIPTION:
Sweetwater Creek Trib 26 4047
END DESCRIPTION:
XS GIS Cut Line= 3
      1389084.33      6863015.29      1389045.72      6862538.45
      1389002.67      6862347.95
#Sta/Elev= 30
  4521.6 2103.44  4528.9 2103.14  4549.0 2104.64  4569.0 2104.00  4574.6 2104.71
  4609.2 2101.88  4669.4 2099.64  4696.8 2099.46  4759.7 2096.90  4779.7 2097.19
  4824.0 2095.52  4940.3 2093.82  4951.2 2092.79  4970.3 2092.58  4980.4 2090.51
  4990.4 2087.17  4995.7 2086.56  4996.0 2086.06  4999.5 2086.06  4999.7 2086.56
  5051.7 2087.45  5117.5 2090.09  5144.0 2093.27  5149.6 2094.93  5154.2 2096.29
  5160.7 2101.56  5165.8 2100.04  5174.7 2106.21  5185.0 2110.74  5195.3 2111.92
#Mann=4,-1,0
  4521.6    0.07       0  4995.7    0.07       0  4999.7    0.07       0
  5149.6   0.035       0
Bank Sta=4995.7,4999.7
Exp/Cntr=0.3,0.1

Type RM Length L Ch R = 1,9374,342,342,342
BEGIN DESCRIPTION:
Sweetwater Creek Trib 26 16.0
END DESCRIPTION:
XS GIS Cut Line= 3
      1390322.48      6862763.22      1389302.58      6862543.96
      1389039.88      6862366.90
#Sta/Elev= 30
  3956.8 2097.01  4002.8 2094.62  4007.9 2090.25  4096.4 2092.47  4244.5 2092.58
  4288.8 2094.43  4293.9 2092.82  4332.7 2094.09  4537.2 2092.14  4567.9 2093.36
  4957.4 2084.65  4957.6 2084.15  4961.4 2084.65  5053.4 2086.59  5059.4 2085.49
  5068.3 2085.75  5074.4 2088.44  5197.3 2089.85  5233.3 2091.77  5239.3 2094.91
  5248.3 2093.62  5254.3 2099.94  5267.6 2097.56  5269.3 2097.25  5275.3 2104.13
  5284.2 2102.07  5290.3 2108.28  5305.2 2105.69  5311.3 2109.58  5316.8 2109.46
#Mann=4,-1,0
  3956.8    0.07       0  4957.4    0.07       0  4961.4    0.07       0
  5267.6   0.035       0
Bank Sta=4957.4,4961.4
Exp/Cntr=0.3,0.1

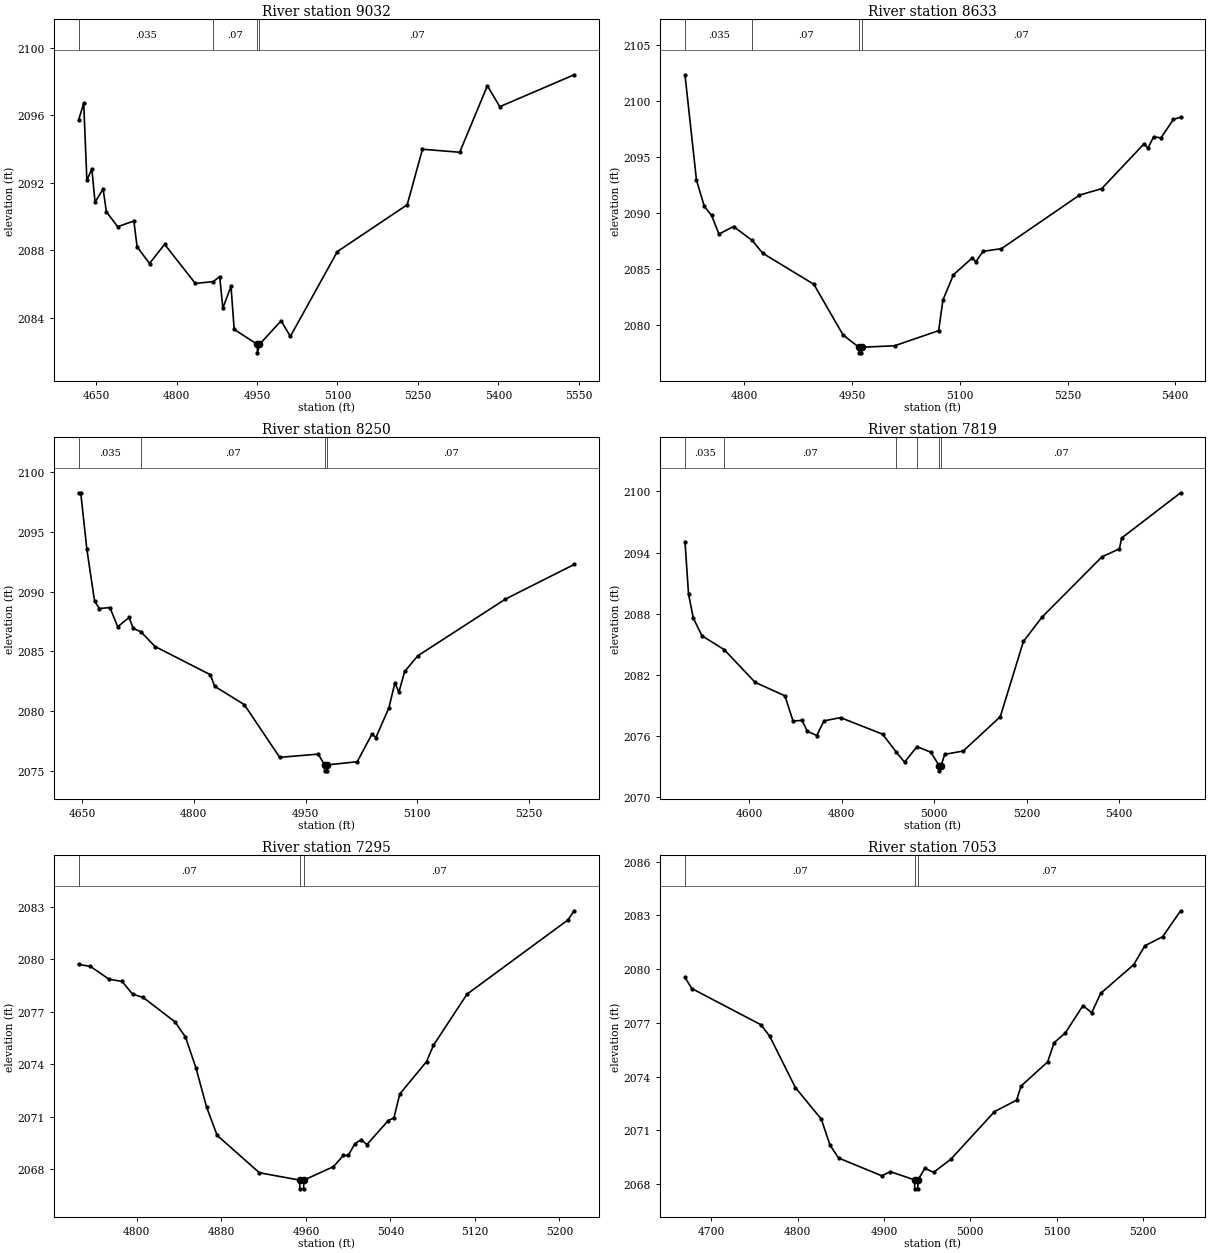
Type RM Length L Ch R = 1,9032,399,399,399
BEGIN DESCRIPTION:
Sweetwater Creek Trib 26 15.0
END DESCRIPTION:
XS GIS Cut Line= 3
      1389805.91      6862499.72      1389478.15      6862285.94
      1388992.78      6862066.23
#Sta/Elev= 30
  4617.2 2095.71  4626.9 2096.71  4632.8 2092.14  4642.0 2092.83  4648.0 2090.86
  4663.1 2091.63  4669.1 2090.29  4690.2 2089.40  4720.4 2089.74  4726.4 2088.21
  4749.6 2087.22  4777.7 2088.36  4835.0 2086.04  4868.4 2086.15  4880.4 2086.44
  4886.3 2084.58  4901.5 2085.87  4907.4 2083.32  4950.6 2082.43  4950.8 2081.93
  4954.6 2082.43  4995.0 2083.83  5012.1 2082.90  5099.8 2087.93  5230.0 2090.70
  5258.5 2093.99  5327.9 2093.81  5379.5 2097.75  5402.6 2096.51  5541.3 2098.40
#Mann=4,-1,0
  4617.2   0.035       0  4868.4    0.07       0  4950.6    0.07       0
  4954.6    0.07       0
Bank Sta=4950.6,4954.6
Exp/Cntr=0.3,0.1

Type RM Length L Ch R = 1,8633,383,383,383
BEGIN DESCRIPTION:
Sweetwater Creek Trib 26 14.0
END DESCRIPTION:
XS GIS Cut Line= 3
      1389826.36      6862514.53      1389878.04      6862231.91
      1389777.99      6861841.53
#Sta/Elev= 30
  4717.2 2102.33  4733.2 2092.94  4744.2 2090.59  4754.3 2089.79  4764.5 2088.13
  4784.8 2088.80  4810.8 2087.56  4825.5 2086.42  4896.7 2083.65  4937.3 2079.14
  4959.3 2078.04  4959.5 2077.54  4963.0 2077.54  4963.3 2078.04  5009.1 2078.17
  5070.5 2079.52  5076.4 2082.24  5091.1 2084.50  5117.2 2086.00  5122.3 2085.66
  5132.4 2086.59  5158.0 2086.83  5266.6 2091.60  5297.6 2092.18  5356.8 2096.19
  5361.9 2095.79  5369.9 2096.79  5380.2 2096.71  5397.5 2098.36  5407.5 2098.54
#Mann=4,-1,0
  4717.2   0.035       0  4810.8    0.07       0  4959.3    0.07       0
  4963.3    0.07       0
Bank Sta=4959.3,4963.3
Exp/Cntr=0.3,0.1

Type RM Length L Ch R = 1,8250,431,431,431
BEGIN DESCRIPTION:
Sweetwater Creek Trib 26 13.0
END DESCRIPTION:
XS GIS Cut Line= 3
      1390152.42      6862588.79      1390244.52      6862246.15
      1390139.68      6861953.89
#Sta/Elev= 30
  4645.2 2098.28  4648.2 2098.28  4656.4 2093.55  4666.7 2089.23  4673.2 2088.59
  4687.4 2088.67  4697.8 2087.06  4713.1 2087.84  4718.5 2086.94  4729.3 2086.62
  4747.9 2085.41  4822.1 2083.05  4827.9 2082.08  4867.8 2080.54  4915.2 2076.13
  4967.0 2076.40  4975.4 2075.50  4975.6 2075.00  4979.1 2075.00  4979.4 2075.50
  5019.3 2075.76  5039.1 2078.08  5044.4 2077.79  5061.8 2080.27  5069.9 2082.37
  5075.2 2081.58  5083.0 2083.32  5100.6 2084.63  5218.3 2089.38  5310.5 2092.28
#Mann=4,-1,0
  4645.2   0.035       0  4729.3    0.07       0  4975.4    0.07       0
  4979.4    0.07       0
Bank Sta=4975.4,4979.4
Exp/Cntr=0.3,0.1

Type RM Length L Ch R = 1,7819,524,524,524
BEGIN DESCRIPTION:
Sweetwater Creek Trib 26 12.0
END DESCRIPTION:
XS GIS Cut Line= 3
      1390480.81      6862655.51      1390604.52      6862132.34
      1390611.76      6861597.89
#Sta/Elev= 30
  4460.7 2095.08  4468.4 2089.92  4478.7 2087.56  4497.4 2085.82  4545.5 2084.46
  4612.3 2081.25  4676.8 2079.92  4694.5 2077.44  4713.9 2077.51  4725.3 2076.44
  4745.9 2076.02  4761.3 2077.46  4797.2 2077.78  4888.2 2076.15  4917.4 2074.41
  4935.6 2073.40  4962.5 2074.93  4992.5 2074.38  5010.6 2073.05  5010.9 2072.55
  5014.6 2073.05  5022.6 2074.17  5062.6 2074.50  5142.7 2077.87  5192.7 2085.26
  5232.7 2087.64  5362.7 2093.58  5400.3 2094.36  5405.3 2095.43  5532.8 2099.87
#Mann=6,-1,0
  4460.7   0.035       0  4545.5    0.07       0  4917.4   0.035       0
  4962.5    0.07       0  5010.6    0.07       0  5014.6    0.07       0
Bank Sta=5010.6,5014.6
Exp/Cntr=0.3,0.1

Type RM Length L Ch R = 1,7295,242,242,242
BEGIN DESCRIPTION:
Sweetwater Creek Trib 26 11.0
END DESCRIPTION:
XS GIS Cut Line= 3
      1391010.81      6862479.19      1391004.33      6862224.07
      1390933.15      6862022.36
#Sta/Elev= 30
  4744.8 2079.71  4756.0 2079.60  4773.8 2078.86  4786.0 2078.74  4796.0 2078.01
  4806.0 2077.82  4836.0 2076.43  4846.0 2075.56  4856.0 2073.78  4866.0 2071.55
  4876.0 2069.93  4916.0 2067.79  4954.1 2067.37  4954.3 2066.87  4957.8 2066.87
  4958.1 2067.37  4986.1 2068.14  4995.5 2068.78  5000.0 2068.78  5006.4 2069.45
  5012.4 2069.69  5017.7 2069.40  5038.0 2070.78  5043.3 2070.93  5048.9 2072.30
  5074.2 2074.15  5080.7 2075.08  5112.5 2078.01  5207.9 2082.25  5213.9 2082.78
#Mann=3,-1,0
  4744.8    0.07       0  4954.1    0.07       0  4958.1    0.07       0
Bank Sta=4954.1,4958.1
Exp/Cntr=0.3,0.1

Type RM Length L Ch R = 1,7053,254,254,254
BEGIN DESCRIPTION:
Sweetwater Creek Trib 26 4046
END DESCRIPTION:
XS GIS Cut Line= 3
      1391122.84      6862485.86      1391121.65      6862155.36
      1391068.67      6861917.59
#Sta/Elev= 30
  4669.5 2079.54  4677.4 2078.92  4757.4 2076.90  4767.4 2076.28  4797.4 2073.39
  4827.4 2071.63  4837.4 2070.19  4847.4 2069.46  4897.4 2068.47  4907.4 2068.70
  4935.4 2068.24  4935.6 2067.74  4939.1 2067.74  4939.4 2068.24  4947.4 2068.89
  4957.4 2068.66  4977.4 2069.39  5028.0 2072.05  5053.6 2072.69  5058.8 2073.48
  5089.5 2074.82  5097.1 2075.90  5110.0 2076.44  5130.5 2077.97  5140.6 2077.57
  5151.0 2078.65  5189.2 2080.25  5202.2 2081.31  5222.7 2081.81  5243.6 2083.26
#Mann=3,-1,0
  4669.5    0.07       0  4935.4    0.07       0  4939.4    0.07       0
Bank Sta=4935.4,4939.4
Exp/Cntr=0.3,0.1

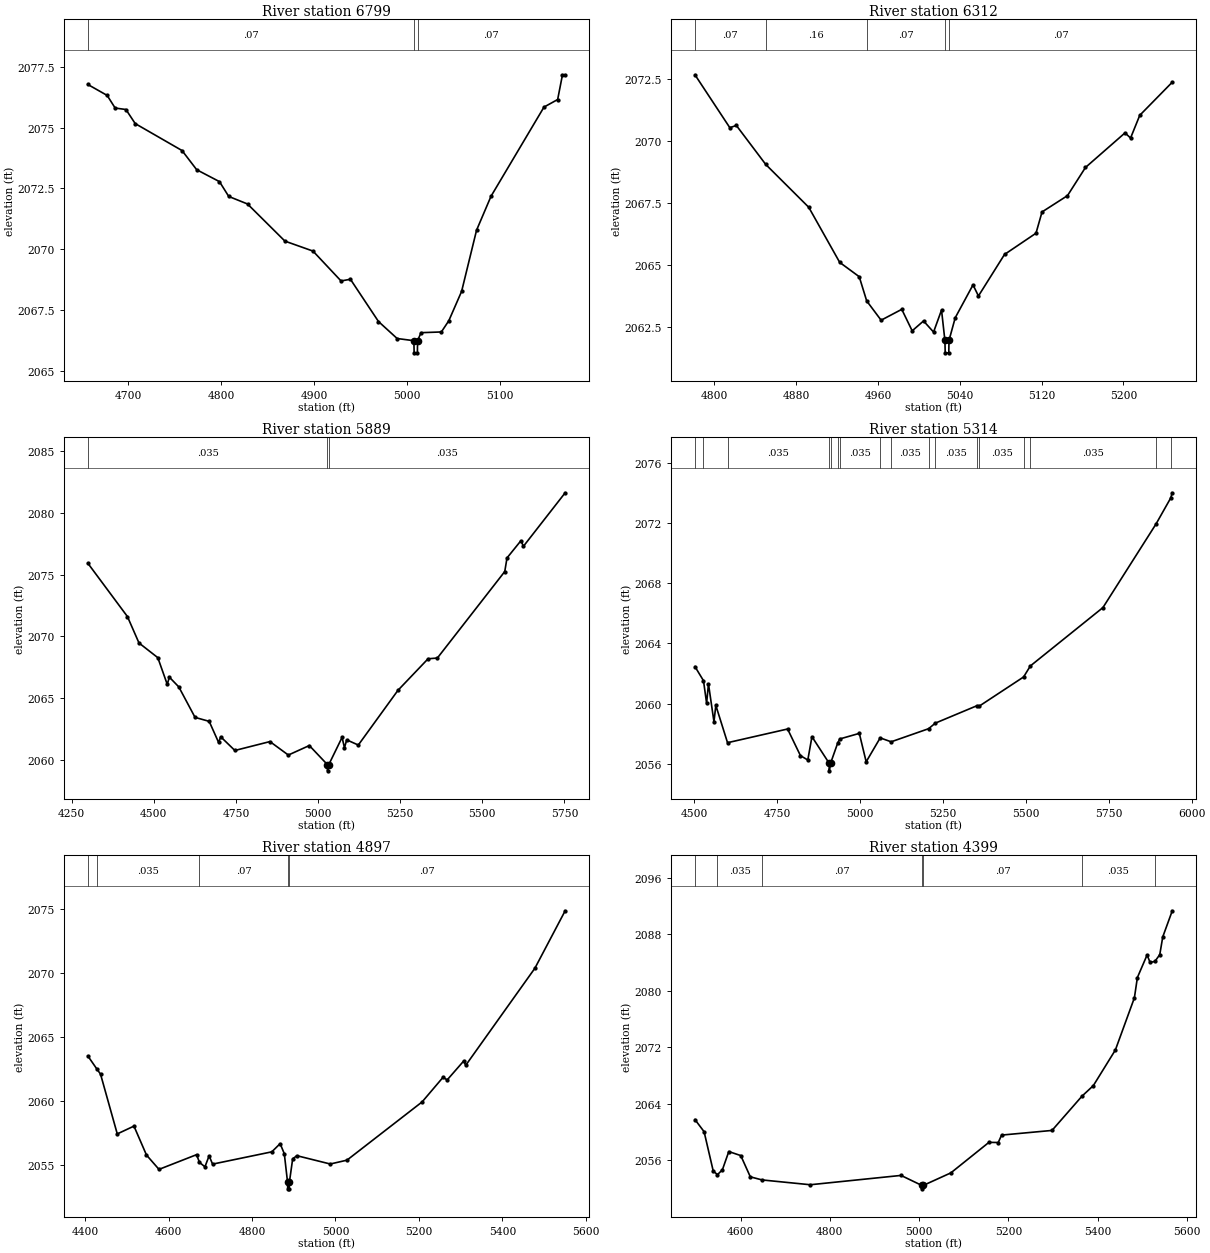
Type RM Length L Ch R = 1,6799,487,487,487
BEGIN DESCRIPTION:
Sweetwater Creek Trib 26 10.0
END DESCRIPTION:
XS GIS Cut Line= 3
      1391296.11      6862428.69      1391336.57      6862087.38
      1391255.00      6861938.00
#Sta/Elev= 30
  4656.3 2076.78  4677.1 2076.33  4685.7 2075.81  4697.3 2075.75  4707.3 2075.17
  4757.7 2074.06  4773.5 2073.27  4798.0 2072.78  4808.0 2072.17  4828.2 2071.86
  4868.5 2070.33  4898.7 2069.92  4928.9 2068.69  4939.0 2068.76  4969.2 2067.02
  4989.3 2066.32  5007.3 2066.23  5007.6 2065.73  5011.1 2065.73  5011.3 2066.23
  5015.0 2066.56  5036.9 2066.59  5044.9 2067.05  5058.7 2068.26  5074.8 2070.78
  5090.4 2072.18  5147.4 2075.85  5162.1 2076.16  5167.3 2077.18  5170.2 2077.18
#Mann=3,-1,0
  4656.3    0.07       0  5007.3    0.07       0  5011.3    0.07       0
Bank Sta=5007.3,5011.3
Exp/Cntr=0.3,0.1

Type RM Length L Ch R = 1,6312,423,423,423
BEGIN DESCRIPTION:
Sweetwater Creek Trib 26 9.0
END DESCRIPTION:
XS GIS Cut Line= 3
      1391705.00      6862437.99      1391738.29      6862221.43
      1391655.02      6861988.05
#Sta/Elev= 30
  4780.9 2072.69  4815.0 2070.55  4821.4 2070.64  4850.2 2069.06  4892.2 2067.33
  4922.5 2065.10  4941.6 2064.52  4948.9 2063.54  4963.0 2062.76  4983.2 2063.20
  4993.4 2062.33  5004.5 2062.73  5014.3 2062.28  5022.1 2063.17  5025.4 2061.94
  5025.7 2061.44  5029.2 2061.44  5029.4 2061.94  5035.5 2062.86  5052.9 2064.19
  5058.2 2063.74  5083.7 2065.42  5114.5 2066.28  5120.4 2067.14  5145.3 2067.80
  5162.9 2068.94  5201.6 2070.34  5207.0 2070.13  5216.0 2071.05  5247.8 2072.39
#Mann=5,-1,0
  4780.9    0.07       0  4850.2    0.16       0  4948.9    0.07       0
  5025.4    0.07       0  5029.4    0.07       0
Bank Sta=5025.4,5029.4
Exp/Cntr=0.3,0.1

Type RM Length L Ch R = 1,5889,575,575,575
BEGIN DESCRIPTION:
Sweetwater Creek Trib 26 8.0
END DESCRIPTION:
XS GIS Cut Line= 3
      1392564.97      6862778.08      1392118.84      6862237.50
      1391605.01      6861688.01
#Sta/Elev= 30
  4299.1 2075.93  4419.6 2071.61  4454.8 2069.47  4512.1 2068.28  4540.8 2066.12
  4547.3 2066.70  4576.0 2065.91  4625.5 2063.44  4668.5 2063.12  4697.2 2061.41
  4703.6 2061.87  4746.7 2060.76  4853.5 2061.48  4909.5 2060.39  4973.4 2061.16
  5028.6 2059.61  5028.8 2059.11  5032.6 2059.61  5073.1 2061.82  5080.4 2060.98
  5087.2 2061.62  5122.5 2061.20  5243.1 2065.63  5334.9 2068.19  5363.2 2068.25
  5568.4 2075.26  5575.2 2076.36  5617.7 2077.76  5625.1 2077.30  5752.3 2081.64
#Mann=3,-1,0
  4299.1   0.035       0  5028.6   0.035       0  5032.6   0.035       0
Bank Sta=5028.6,5032.6
Exp/Cntr=0.3,0.1

Type RM Length L Ch R = 1,5314,417,417,417
BEGIN DESCRIPTION:
Sweetwater Creek Trib 26 7.0
END DESCRIPTION:
XS GIS Cut Line= 3
      1392747.16      6862582.19      1392519.91      6862138.39
      1391838.79      6861488.39
#Sta/Elev= 30
  4501.4 2062.46  4527.2 2061.52  4536.6 2060.02  4542.2 2061.31  4558.8 2058.79
  4564.4 2059.88  4599.7 2057.40  4780.9 2058.31  4819.7 2056.54  4841.9 2056.25
  4854.4 2057.80  4906.5 2056.03  4906.7 2055.53  4910.5 2056.03  4932.0 2057.37
  4938.5 2057.65  4997.3 2058.02  5018.0 2056.13  5060.3 2057.72  5093.4 2057.46
  5206.3 2058.33  5226.6 2058.70  5352.4 2059.86  5359.8 2059.84  5493.0 2061.77
  5513.3 2062.50  5732.3 2066.38  5892.6 2071.94  5936.7 2073.66  5941.5 2074.01
#Mann=17,-1,0
  4501.4   0.035       0  4527.2   0.063       0  4599.7   0.035       0
  4906.5   0.035       0  4910.5   0.035       0  4932.0    0.07       0
  4938.5   0.035       0  5060.3    0.07       0  5093.4   0.035       0
  5206.3    0.07       0  5226.6   0.035       0  5352.4    0.07       0
  5359.8   0.035       0  5493.0   0.094       0  5513.3   0.035       0
  5892.6   0.094       0  5936.7   0.035       0
Bank Sta=4906.5,4910.5
Exp/Cntr=0.3,0.1

Type RM Length L Ch R = 1,4897,498,498,498
BEGIN DESCRIPTION:
Sweetwater Creek Trib 26 6.0
END DESCRIPTION:
XS GIS Cut Line= 3
      1392777.90      6862638.41      1392801.65      6862045.58
      1392781.07      6861495.47
#Sta/Elev= 30
  4406.7 2063.55  4428.3 2062.53  4437.1 2062.13  4477.2 2057.46  4517.2 2058.07
  4547.2 2055.81  4577.2 2054.69  4667.3 2055.84  4674.1 2055.24  4687.3 2054.89
  4697.3 2055.75  4705.6 2055.10  4847.5 2056.06  4867.5 2056.70  4877.5 2055.91
  4885.3 2053.67  4885.6 2053.17  4889.3 2053.17  4889.6 2053.67  4897.5 2055.51
  4907.5 2055.76  4987.6 2055.11  5027.6 2055.41  5207.7 2059.96  5257.8 2061.88
  5267.8 2061.68  5307.2 2063.15  5312.2 2062.82  5477.9 2070.40  5550.5 2074.89
#Mann=5,-1,0
  4406.7   0.063       0  4428.3   0.035       0  4674.1    0.07       0
  4885.3    0.07       0  4889.6    0.07       0
Bank Sta=4885.3,4889.6
Exp/Cntr=0.3,0.1

Type RM Length L Ch R = 1,4399,475,475,475
BEGIN DESCRIPTION:
Sweetwater Creek Trib 26 5.0
END DESCRIPTION:
XS GIS Cut Line= 3
      1393063.43      6862848.01      1393174.83      6862358.42
      1393554.99      6861938.01
#Sta/Elev= 30
  4497.9 2061.76  4518.4 2060.04  4538.9 2054.46  4548.4 2053.96  4559.4 2054.65
  4573.7 2057.23  4600.5 2056.66  4621.9 2053.65  4648.2 2053.21  4756.1 2052.53
  4959.4 2053.85  5005.4 2052.45  5005.7 2051.95  5009.7 2052.45  5071.0 2054.21
  5156.2 2058.53  5177.1 2058.51  5184.6 2059.56  5297.5 2060.22  5364.6 2065.07
  5390.1 2066.57  5439.4 2071.61  5482.0 2079.00  5488.7 2081.87  5510.4 2085.06
  5517.1 2084.01  5527.9 2084.15  5538.8 2085.11  5545.5 2087.62  5566.8 2091.32
#Mann=7,-1,0
  4497.9   0.063       0  4548.4   0.035       0  4648.2    0.07       0
  5005.4    0.07       0  5009.7    0.07       0  5364.6   0.035       0
  5527.9    0.07       0
Bank Sta=5005.4,5009.7
Exp/Cntr=0.3,0.1

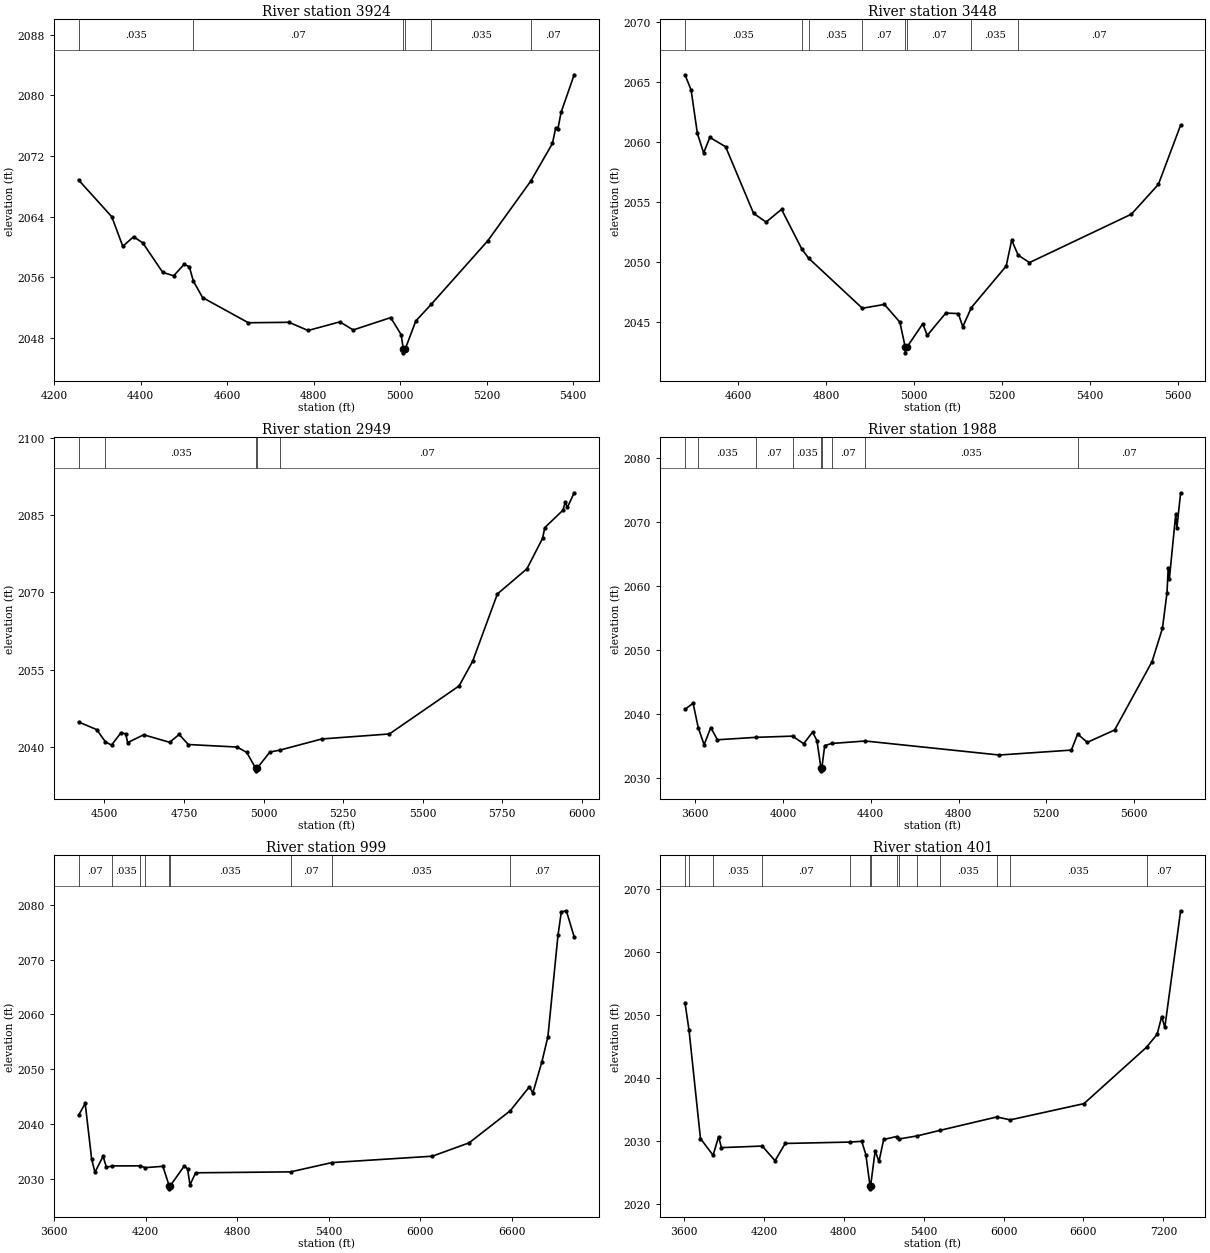
Type RM Length L Ch R = 1,3924,476,476,476
BEGIN DESCRIPTION:
Sweetwater Creek Trib 26 4.0
END DESCRIPTION:
XS GIS Cut Line= 3
      1393355.01      6863187.98      1393605.31      6862487.67
      1393654.99      6862088.04
#Sta/Elev= 30
  4256.3 2068.83  4333.2 2063.98  4358.7 2060.07  4383.7 2061.33  4405.0 2060.52
  4451.1 2056.63  4476.5 2056.18  4500.5 2057.69  4512.6 2057.38  4521.8 2055.49
  4543.4 2053.30  4649.2 2049.98  4743.0 2050.04  4787.3 2048.96  4860.8 2050.10
  4891.6 2049.03  4978.4 2050.66  5002.4 2048.42  5007.6 2046.51  5007.8 2046.01
  5011.9 2046.51  5036.5 2050.22  5072.2 2052.42  5203.2 2060.82  5302.3 2068.68
  5352.4 2073.64  5359.8 2075.64  5364.8 2075.49  5372.5 2077.76  5402.7 2082.71
#Mann=6,-1,0
  4256.3   0.035       0  4521.8    0.07       0  5007.6    0.07       0
  5011.9    0.07       0  5072.2   0.035       0  5302.3    0.07       0
Bank Sta=5007.6,5011.9
Exp/Cntr=0.3,0.1

Type RM Length L Ch R = 1,3448,499,499,499
BEGIN DESCRIPTION:
Sweetwater Creek Trib 26 3.0
END DESCRIPTION:
XS GIS Cut Line= 3
      1393504.97      6863188.03      1393889.64      6862837.83
      1393805.00      6862237.98
#Sta/Elev= 30
  4479.8 2065.58  4493.7 2064.32  4507.9 2060.72  4522.1 2059.08  4536.3 2060.37
  4572.1 2059.59  4635.6 2054.05  4664.0 2053.32  4699.1 2054.38  4745.5 2051.06
  4760.9 2050.31  4882.7 2046.15  4932.9 2046.47  4968.0 2044.99  4980.0 2042.94
  4980.3 2042.44  4984.5 2042.94  5020.0 2044.86  5030.1 2043.89  5072.3 2045.75
  5100.8 2045.71  5110.9 2044.61  5130.4 2046.21  5209.5 2049.66  5222.0 2051.82
  5236.7 2050.57  5262.4 2049.95  5494.0 2053.98  5555.3 2056.46  5605.8 2061.39
#Mann=8,-1,0
  4479.8   0.035       0  4745.5    0.07       0  4760.9   0.035       0
  4882.7    0.07       0  4980.0    0.07       0  4984.5    0.07       0
  5130.4   0.035       0  5236.7    0.07       0
Bank Sta=4980,4984.5
Exp/Cntr=0.3,0.1

Type RM Length L Ch R = 1,2949,961,961,961
BEGIN DESCRIPTION:
Sweetwater Creek Trib 26 2.0
END DESCRIPTION:
XS GIS Cut Line= 4
      1394299.98      6863253.93      1394377.39      6863193.31
      1394305.24      6862715.45      1393655.00      6861988.00
#Sta/Elev= 30
  4418.4 2044.87  4475.6 2043.37  4503.1 2040.99  4522.1 2040.37  4552.4 2042.81
  4566.9 2042.52  4572.7 2040.85  4623.2 2042.37  4704.7 2040.91  4734.5 2042.43
  4763.5 2040.48  4916.5 2039.99  4946.9 2038.96  4974.9 2035.87  4975.2 2035.37
  4979.4 2035.87  5019.8 2039.03  5050.3 2039.38  5182.8 2041.56  5395.1 2042.53
  5614.2 2051.86  5656.8 2056.66  5734.5 2069.72  5827.3 2074.60  5876.6 2080.53
  5883.3 2082.59  5940.2 2085.96  5947.7 2087.54  5954.4 2086.52  5975.7 2089.36
#Mann=5,-1,0
  4418.4    0.07       0  4503.1   0.035       0  4974.9   0.035       0
  4979.4   0.035       0  5050.3    0.07       0
Bank Sta=4974.9,4979.4
Exp/Cntr=0.3,0.1

Type RM Length L Ch R = 1,1988,989,989,989
BEGIN DESCRIPTION:
Sweetwater Creek Trib 26 1.0
END DESCRIPTION:
XS GIS Cut Line= 4
      1394783.31      6863324.58      1394623.25      6862110.83
      1394538.40      6861904.78      1393755.04      6861688.01
#Sta/Elev= 30
  3552.9 2040.74  3589.8 2041.70  3613.2 2037.90  3640.2 2035.21  3670.5 2037.90
  3700.8 2035.99  3875.8 2036.37  4043.2 2036.56  4094.1 2035.38  4134.5 2037.18
  4154.6 2035.87  4172.5 2031.64  4172.9 2031.14  4177.1 2031.64  4190.0 2035.08
  4221.3 2035.41  4374.5 2035.80  4985.7 2033.61  5314.8 2034.38  5343.0 2036.88
  5387.4 2035.59  5511.9 2037.52  5682.4 2048.19  5729.8 2053.38  5750.6 2058.94
  5756.2 2062.89  5761.4 2061.10  5790.5 2071.22  5795.7 2069.08  5812.8 2074.56
#Mann=9,-1,0
  3552.9    0.07       0  3613.2   0.035       0  3875.8    0.07       0
  4043.2   0.035       0  4172.5   0.035       0  4177.1   0.035       0
  4221.3    0.07       0  4374.5   0.035       0  5343.0    0.07       0
Bank Sta=4172.5,4177.1
Exp/Cntr=0.3,0.1

Type RM Length L Ch R = 1,999,598,598,598
BEGIN DESCRIPTION:
Sweetwater Creek Trib 26 358
END DESCRIPTION:
XS GIS Cut Line= 5
      1395048.64      6863389.10      1395369.84      6862510.96
      1395388.24      6862205.35      1395364.28      6861984.43
      1393738.34      6861245.24
#Sta/Elev= 30
  3758.8 2041.62  3802.6 2043.81  3845.0 2033.67  3866.5 2031.28  3919.7 2034.18
  3941.9 2032.18  3979.2 2032.43  4163.3 2032.45  4196.0 2032.12  4312.1 2032.36
  4353.8 2028.76  4354.2 2028.26  4358.7 2028.76  4452.1 2032.42  4473.4 2031.90
  4489.9 2028.99  4526.6 2031.18  5149.6 2031.35  5420.0 2033.04  6078.2 2034.20
  6319.9 2036.64  6588.3 2042.45  6715.4 2046.85  6737.3 2045.70  6797.0 2051.41
  6836.2 2055.99  6902.1 2074.38  6924.1 2078.69  6957.0 2078.88  7008.3 2074.13
#Mann=9,-1,0
  3758.8    0.07       0  3979.2   0.035       0  4163.3    0.07       0
  4196.0   0.035       0  4353.8   0.035       0  4358.7   0.035       0
  5149.6    0.07       0  5420.0   0.035       0  6588.3    0.07       0
Bank Sta=4353.8,4358.7
Exp/Cntr=0.3,0.1

Type RM Length L Ch R = 1,401,0,0,0
BEGIN DESCRIPTION:
Sweetwater Creek Trib 26 4091
END DESCRIPTION:
XS GIS Cut Line= 4
      1395373.01      6863676.48      1395831.53      6862361.11
      1395478.33      6861913.59      1393863.17      6861214.95
#Sta/Elev= 30
  3607.0 2051.92  3637.7 2047.50  3723.3 2030.38  3818.2 2027.73  3859.6 2030.68
  3880.7 2028.94  4187.4 2029.19  4283.2 2026.87  4360.0 2029.60  4845.7 2029.82
  4934.5 2029.94  4965.6 2027.84  4996.5 2022.91  4996.9 2022.41  5001.5 2022.91
  5035.3 2028.42  5064.2 2026.75  5099.4 2030.23  5196.0 2030.70  5217.0 2030.32
  5351.6 2030.80  5521.0 2031.67  5949.3 2033.80  6050.3 2033.34  6603.8 2035.91
  7074.0 2044.85  7153.3 2046.91  7187.7 2049.70  7211.2 2048.00  7329.9 2066.47
#Mann=14,-1,0
  3607.0   0.035       0  3637.7    0.07       0  3818.2   0.035       0
  4187.4    0.07       0  4845.7   0.035       0  4996.5   0.035       0
  5001.5   0.035       0  5196.0    0.07       0  5217.0   0.035       0
  5351.6    0.07       0  5521.0   0.035       0  5949.3    0.07       0
  6050.3   0.035       0  7074.0    0.07       0
Bank Sta=4996.5,5001.5
Exp/Cntr=0.3,0.1

Chan Stop Cuts=-1