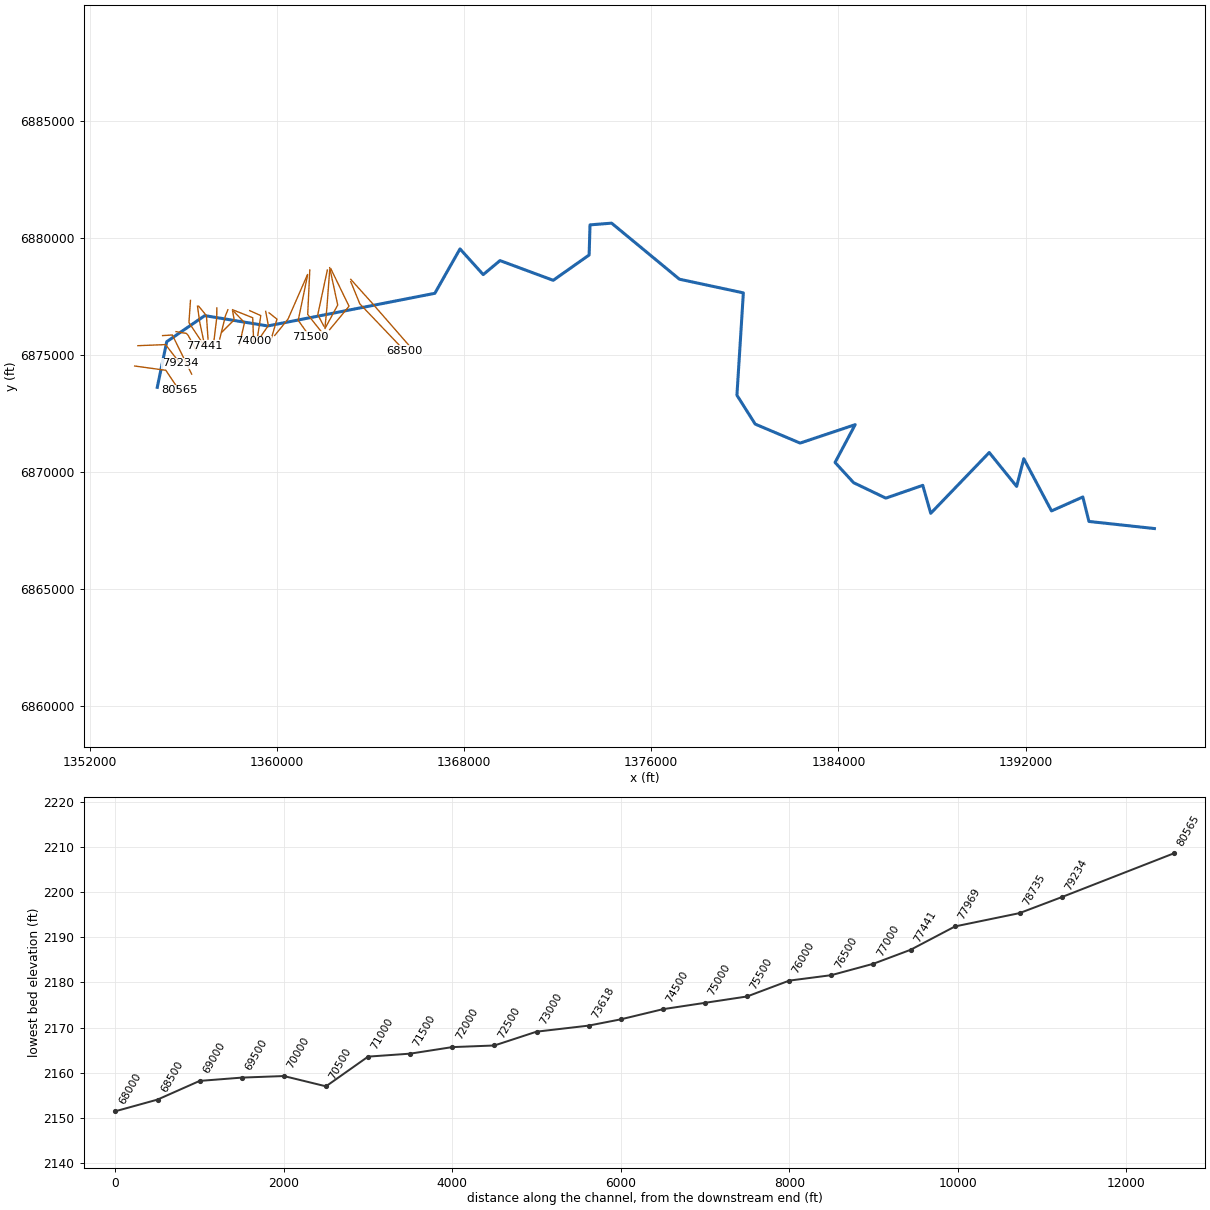
--- Sweetwater Creek Trib 27.prj (project) ---

Proj Title=Sweetwater Creek Trib 27 Base Level Engineering
Current Plan=p01
Default Exp/Contr=0.3,0.1
English Units
Geom File=g01
Flow File=f01
Plan File=p01
Y Axis Title=Elevation
X Axis Title(PF)=Main Channel Distance
X Axis Title(XS)=Station
BEGIN DESCRIPTION:
Sweetwater Creek Trib 27
END DESCRIPTION:
DSS Export Rating Curves= 0
DSS Export Rating Curve Sorted= 0
DSS Export Volume Flow Curves= 0
DXF OffsetX= 0
DXF OffsetY= 0
DXF ScaleX= 1
DXF ScaleY= 10

--- Sweetwater Creek Trib 27.p01 (plan) ---

Plan Title=Multiple Run
Short Identifier=Multiple
Geom File=g01
Flow File=f01
Subcritical Flow
K Sum by GR= 0
Std Step Tol= 0.01
Critical Tol= 0.01
Num of Std Step Trials= 20
Max Error Tol= 0.3
Flow Tol Ratio= 0.001
Split Flow NTrial= 30
Split Flow Tol= 0.02
Split Flow Ratio= 0.02
Log Output Level= 0
Friction Slope Method= 1
Unsteady Friction Slope Method= 2
Unsteady Bridges Friction Slope Method= 1
Parabolic Critical Depth
Global Vel Dist=  1 , 1 , 1
Global Log Level= 0
CheckData=True
Encroach Param= -1, 0, 0, 0
BEGIN DESCRIPTION:
Multiple Run
END DESCRIPTION:

--- Sweetwater Creek Trib 27.f01 (steady flow) ---

Flow Title=Multiple
Program Version=4.10
Number of Profiles= 7
Profile Names=10-year,25-year,50-year,1pct_min,100-year,1pct_plu,500-year
River Rch & RM=Sweetwater Creek,Reach-1         ,80565
     613     919    1190     765    1527    3047    2551
River Rch & RM=Sweetwater Creek,Reach-1         ,72000
    1147    1730    2250    1448    2889    5764    4832
River Rch & RM=Sweetwater Creek,Reach-1         ,61000
    1184    1776    2300    1473    2940    5865    4870
River Rch & RM=Sweetwater Creek,Reach-1         ,48000
    1742    2646    3455    2230    4449    8877    7482
River Rch & RM=Sweetwater Creek,Reach-1         ,44500
    2765    4305    5719    3753    7489   14943   13021
River Rch & RM=Sweetwater Creek,Reach-1         ,42774
    2812    4377    5816    3817    7616   15196   13243
River Rch & RM=Sweetwater Creek,Reach-1         ,41500
    2902    4526    6020    3955    7892   15746   13751
River Rch & RM=Sweetwater Creek,Reach-1         ,41000
    2999    4677    6221    4087    8155   16272   14210
River Rch & RM=Sweetwater Creek,Reach-1         ,38000
    3040    4742    6309    4145    8271   16503   14413
River Rch & RM=Sweetwater Creek,Reach-1         ,37500
    3027    4713    6261    4108    8197   16355   14244
River Rch & RM=Sweetwater Creek,Reach-1         ,30968
    3016    4691    6229    4084    8150   16260   14142
River Rch & RM=Sweetwater Creek,Reach-1         ,28500
    3067    4772    6338    4157    8294   16548   14399
River Rch & RM=Sweetwater Creek,Reach-1         ,26000
    3036    4718    6260    4102    8184   16330   14182
River Rch & RM=Sweetwater Creek,Reach-1         ,23500
    3418    5326    7082    4649    9276   18508   16131
River Rch & RM=Sweetwater Creek,Reach-1         ,21500
    3449    5372    7139    4685    9347   18649   16239
River Rch & RM=Sweetwater Creek,Reach-1         ,18000
    3424    5326    7072    4636    9250   18456   16040
River Rch & RM=Sweetwater Creek,Reach-1         ,14500
    3708    5755    7632    4997    9971   19895   17237
River Rch & RM=Sweetwater Creek,Reach-1         ,8000
    3743    5811    7709    5049   10073   20099   17423
River Rch & RM=Sweetwater Creek,Reach-1         ,7500
    3655    5654    7482    4888    9752   19458   16779
River Rch & RM=Sweetwater Creek,Reach-1         ,3000
    3618    5590    7390    4823    9623   19201   16525
Boundary for River Rch & Prof#=Sweetwater Creek,Reach-1         , 1
Up Type= 0
Dn Type= 3
Dn Slope=0.005
Boundary for River Rch & Prof#=Sweetwater Creek,Reach-1         , 2
Up Type= 0
Dn Type= 3
Dn Slope=0.005
Boundary for River Rch & Prof#=Sweetwater Creek,Reach-1         , 3
Up Type= 0
Dn Type= 3
Dn Slope=0.005
Boundary for River Rch & Prof#=Sweetwater Creek,Reach-1         , 4
Up Type= 0
Dn Type= 3
Dn Slope=0.005
Boundary for River Rch & Prof#=Sweetwater Creek,Reach-1         , 5
Up Type= 0
Dn Type= 3
Dn Slope=0.005
Boundary for River Rch & Prof#=Sweetwater Creek,Reach-1         , 6
Up Type= 0
Dn Type= 3
Dn Slope=0.005
Boundary for River Rch & Prof#=Sweetwater Creek,Reach-1         , 7
Up Type= 0
Dn Type= 3
Dn Slope=0.005
DSS Import GetInterval= 0
DSS Import GetPeak= 0
DSS Import FillOption= 0

--- Sweetwater Creek Trib 27.g01 (geometry) ---

Geom Title=Existing Conditions

River Reach=Sweetwater Creek,Reach-1
Reach XY= 30
      1354885.61      6873623.47      1355290.23      6875572.85
      1356916.58      6876686.61      1359604.67      6876245.18
      1366749.07      6877640.23      1367824.54      6879538.46
      1368816.88      6878439.51      1369534.92      6879038.33
      1371808.41      6878195.77      1373343.91      6879277.91
      1373381.48      6880565.12      1374305.00      6880638.00
      1377202.73      6878243.31      1379935.58      6877659.03
      1379660.52      6873285.56      1380441.67      6872051.41
      1382360.93      6871240.24      1384714.80      6872027.52
      1383854.68      6870413.11      1384648.34      6869547.30
      1386025.16      6868887.53      1387603.53      6869434.45
      1387944.35      6868239.04      1390444.50      6870836.80
      1391615.29      6869388.59      1391921.75      6870571.60
      1393106.22      6868341.43      1394444.30      6868937.30
      1394706.25      6867891.51      1397505.00      6867588.00

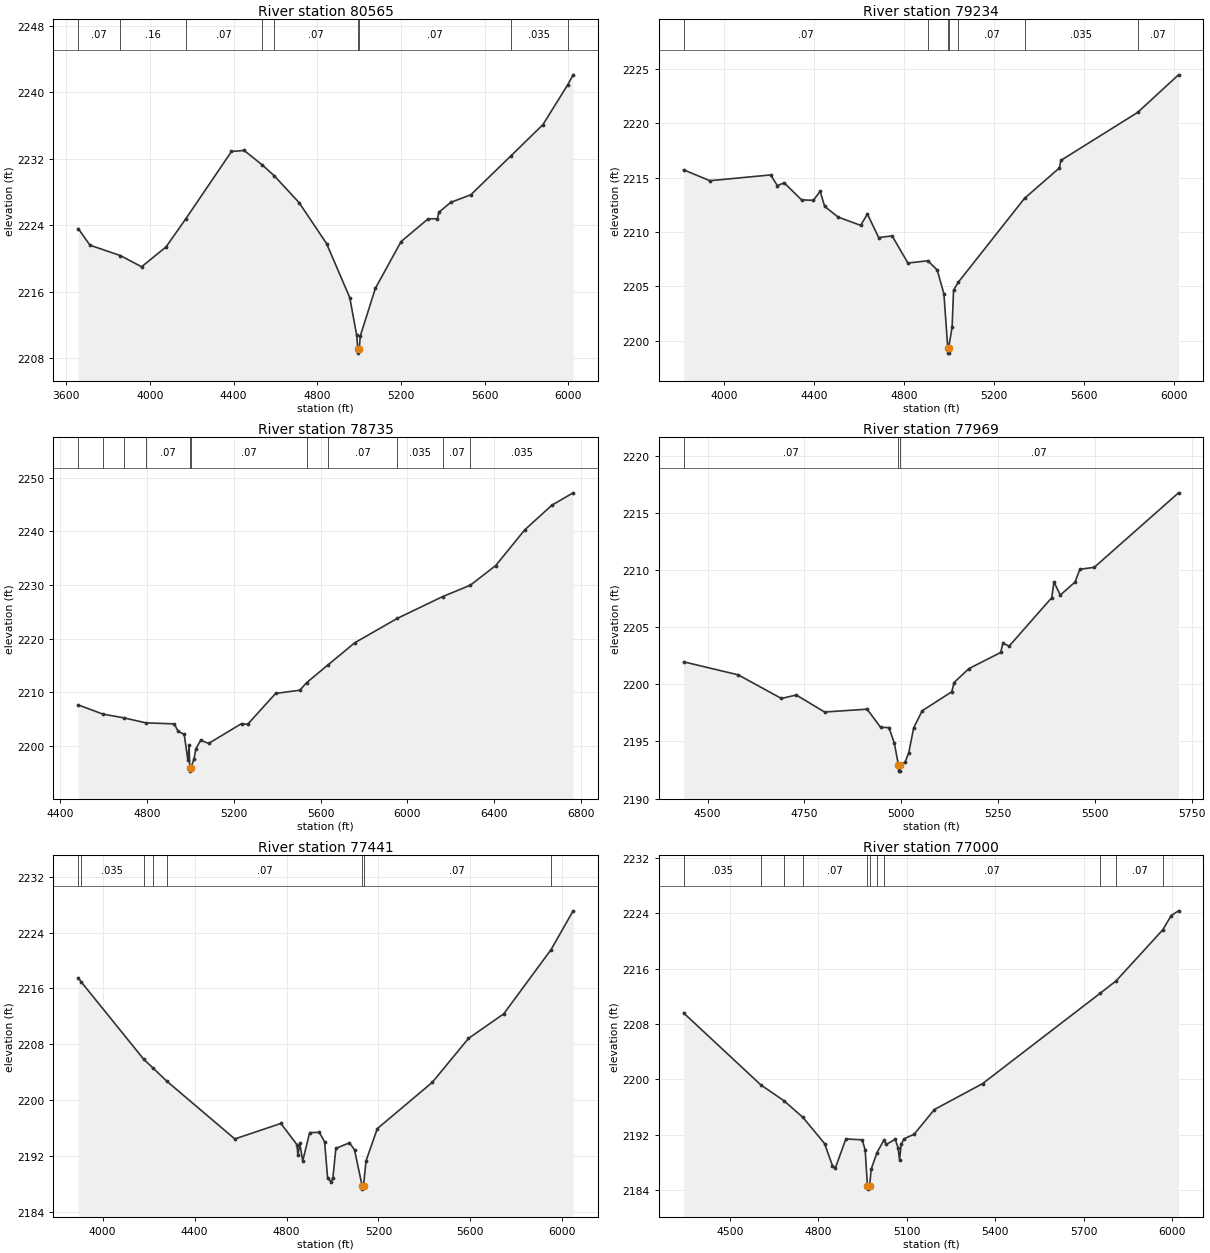
Type RM Length L Ch R = 1,80565,1331,1331,1331
BEGIN DESCRIPTION:
Sweetwater Creek Trib 27 158.0
END DESCRIPTION:
XS GIS Cut Line= 3
      1353919.03      6874534.22      1355249.78      6874351.06
      1355819.45      6873502.19
#Sta/Elev= 30
  3656.7 2223.59  3713.2 2221.58  3858.4 2220.33  3959.8 2218.98  4076.6 2221.37
  4171.7 2224.78  4389.5 2232.87  4450.1 2232.99  4537.0 2231.24  4594.7 2229.92
  4712.5 2226.71  4843.9 2221.78  4954.8 2215.27  4987.9 2210.73  4993.1 2209.08
  4993.3 2208.58  4997.1 2209.08  5000.0 2209.08  5005.0 2210.63  5077.1 2216.38
  5200.1 2222.02  5329.1 2224.75  5374.1 2224.77  5380.1 2225.53  5437.2 2226.74
  5533.2 2227.65  5725.4 2232.35  5878.3 2236.11  5997.2 2240.93  6022.3 2242.10
#Mann=9,-1,0
  3656.7    0.07       0  3858.4    0.16       0  4171.7    0.07       0
  4537.0   0.035       0  4594.7    0.07       0  4993.1    0.07       0
  4997.1    0.07       0  5725.4   0.035       0  5997.2    0.07       0
Bank Sta=4993.1,4997.1
Exp/Cntr=0.3,0.1

Type RM Length L Ch R = 1,79234,499,499,499
BEGIN DESCRIPTION:
Sweetwater Creek Trib 27 157.0
END DESCRIPTION:
XS GIS Cut Line= 3
      1354057.96      6875402.27      1355238.15      6875448.71
      1355863.05      6874642.43
#Sta/Elev= 30
  3818.9 2215.71  3936.0 2214.71  4206.2 2215.24  4236.3 2214.25  4266.3 2214.52
  4343.7 2212.95  4396.4 2212.91  4426.4 2213.74  4446.4 2212.35  4506.5 2211.37
  4606.5 2210.61  4636.6 2211.65  4686.6 2209.49  4746.7 2209.64  4816.7 2207.15
  4905.2 2207.36  4946.8 2206.52  4976.8 2204.33  4993.9 2199.38  4994.2 2198.88
  4997.7 2198.88  4997.9 2199.38  5013.3 2201.28  5019.6 2204.66  5040.4 2205.38
  5335.2 2213.09  5490.4 2215.88  5496.7 2216.57  5838.5 2220.98  6020.1 2224.43
#Mann=7,-1,0
  3818.9    0.07       0  4905.2    0.16       0  4993.9    0.07       0
  4997.9    0.16       0  5040.4    0.07       0  5335.2   0.035       0
  5838.5    0.07       0
Bank Sta=4993.9,4997.9
Exp/Cntr=0.3,0.1

Type RM Length L Ch R = 1,78735,766,766,766
BEGIN DESCRIPTION:
Sweetwater Creek Trib 27 156.0
END DESCRIPTION:
XS GIS Cut Line= 4
      1355113.59      6875833.18      1355531.43      6875859.68
      1355574.16      6875769.47      1356354.98      6874188.03
#Sta/Elev= 30
  4481.5 2207.68  4595.1 2205.97  4694.1 2205.25  4793.2 2204.34  4924.9 2204.14
  4942.2 2202.75  4970.4 2202.21  4987.7 2197.35  4993.2 2200.15  4996.0 2195.85
  4996.3 2195.35  5000.0 2195.85  5015.8 2197.63  5023.9 2199.47  5046.3 2201.09
  5083.1 2200.51  5234.7 2204.19  5262.7 2204.05  5391.8 2209.81  5503.5 2210.41
  5534.5 2211.80  5631.7 2215.07  5756.5 2219.23  5952.0 2223.76  6161.7 2227.83
  6289.9 2229.96  6406.9 2233.62  6540.7 2240.26  6665.5 2244.84  6763.7 2247.15
#Mann=11,-1,0
  4481.5   0.035       0  4595.1    0.07       0  4694.1    0.16       0
  4793.2    0.07       0  4996.0    0.07       0  5000.0    0.07       0
  5534.5   0.035       0  5631.7    0.07       0  5952.0   0.035       0
  6161.7    0.07       0  6289.9   0.035       0
Bank Sta=4996,5000
Exp/Cntr=0.3,0.1

Type RM Length L Ch R = 1,77969,528,528,528
BEGIN DESCRIPTION:
Sweetwater Creek Trib 27 155.0
END DESCRIPTION:
XS GIS Cut Line= 4
      1355686.06      6876003.02      1356128.14      6875926.75
      1356206.86      6875845.27      1356543.24      6875213.10
#Sta/Elev= 30
  4438.1 2201.98  4579.1 2200.84  4690.7 2198.77  4729.3 2199.07  4802.3 2197.58
  4912.0 2197.83  4947.2 2196.23  4968.4 2196.22  4982.5 2194.84  4993.1 2192.90
  4993.3 2192.40  4996.8 2192.40  4997.1 2192.90  5010.3 2193.19  5019.6 2194.02
  5032.3 2196.19  5054.2 2197.69  5130.8 2199.36  5136.5 2200.16  5174.7 2201.38
  5257.0 2202.80  5262.6 2203.61  5278.9 2203.36  5388.8 2207.60  5394.5 2208.98
  5410.8 2207.83  5449.0 2208.97  5461.3 2210.09  5498.6 2210.26  5716.1 2216.79
#Mann=3,-1,0
  4438.1    0.07       0  4993.1    0.07       0  4997.1    0.07       0
Bank Sta=4993.1,4997.1
Exp/Cntr=0.3,0.1

Type RM Length L Ch R = 1,77441,441,441,441
BEGIN DESCRIPTION:
Sweetwater Creek Trib 27 154.0
END DESCRIPTION:
XS GIS Cut Line= 3
      1356305.00      6877338.00      1356238.87      6876388.41
      1356905.01      6875387.99
#Sta/Elev= 30
  3893.3 2217.53  3905.5 2216.99  4179.3 2205.82  4220.4 2204.55  4280.6 2202.66
  4574.9 2194.42  4775.4 2196.64  4845.2 2193.61  4849.5 2192.09  4857.7 2193.77
  4870.5 2191.27  4900.6 2195.32  4942.6 2195.37  4965.8 2194.00  4978.7 2188.83
  4993.7 2188.24  5001.9 2188.88  5014.7 2193.06  5073.9 2193.87  5095.9 2192.85
  5128.9 2187.72  5129.4 2187.22  5135.0 2187.72  5146.0 2191.28  5195.1 2195.90
  5434.4 2202.54  5591.8 2208.84  5745.1 2212.36  5951.2 2221.58  6047.1 2227.14
#Mann=8,-1,0
  3893.3    0.07       0  3905.5   0.035       0  4179.3    0.07       0
  4220.4   0.035       0  4280.6    0.07       0  5128.9    0.07       0
  5135.0    0.07       0  5951.2   0.035       0
Bank Sta=5128.9,5135
Exp/Cntr=0.3,0.1

Type RM Length L Ch R = 1,77000,500,500,500
BEGIN DESCRIPTION:
Sweetwater Creek Trib 27 153.0
END DESCRIPTION:
XS GIS Cut Line= 3
      1356605.00      6877087.98      1356694.57      6876437.02
      1356904.99      6875438.04
#Sta/Elev= 30
  4342.9 2209.62  4605.6 2199.18  4682.8 2196.93  4747.5 2194.51  4821.1 2190.72
  4847.6 2187.53  4857.7 2187.20  4893.1 2191.39  4948.5 2191.26  4958.6 2189.82
  4966.3 2184.63  4966.8 2184.13  4974.0 2184.63  4978.8 2186.99  4998.8 2189.42
  5021.8 2191.19  5030.6 2190.60  5060.3 2191.34  5070.1 2190.14  5075.3 2188.33
  5080.7 2190.64  5091.0 2191.41  5125.1 2192.09  5193.2 2195.64  5356.7 2199.39
  5754.8 2212.44  5809.1 2214.24  5967.7 2221.64  5996.0 2223.69  6020.9 2224.38
#Mann=11,-1,0
  4342.9   0.035       0  4605.6    0.07       0  4682.8   0.035       0
  4747.5    0.07       0  4966.3    0.07       0  4974.0    0.07       0
  4998.8    0.16       0  5021.8    0.07       0  5754.8   0.035       0
  5809.1    0.07       0  5967.7   0.035       0
Bank Sta=4966.3,4974
Exp/Cntr=0.3,0.1

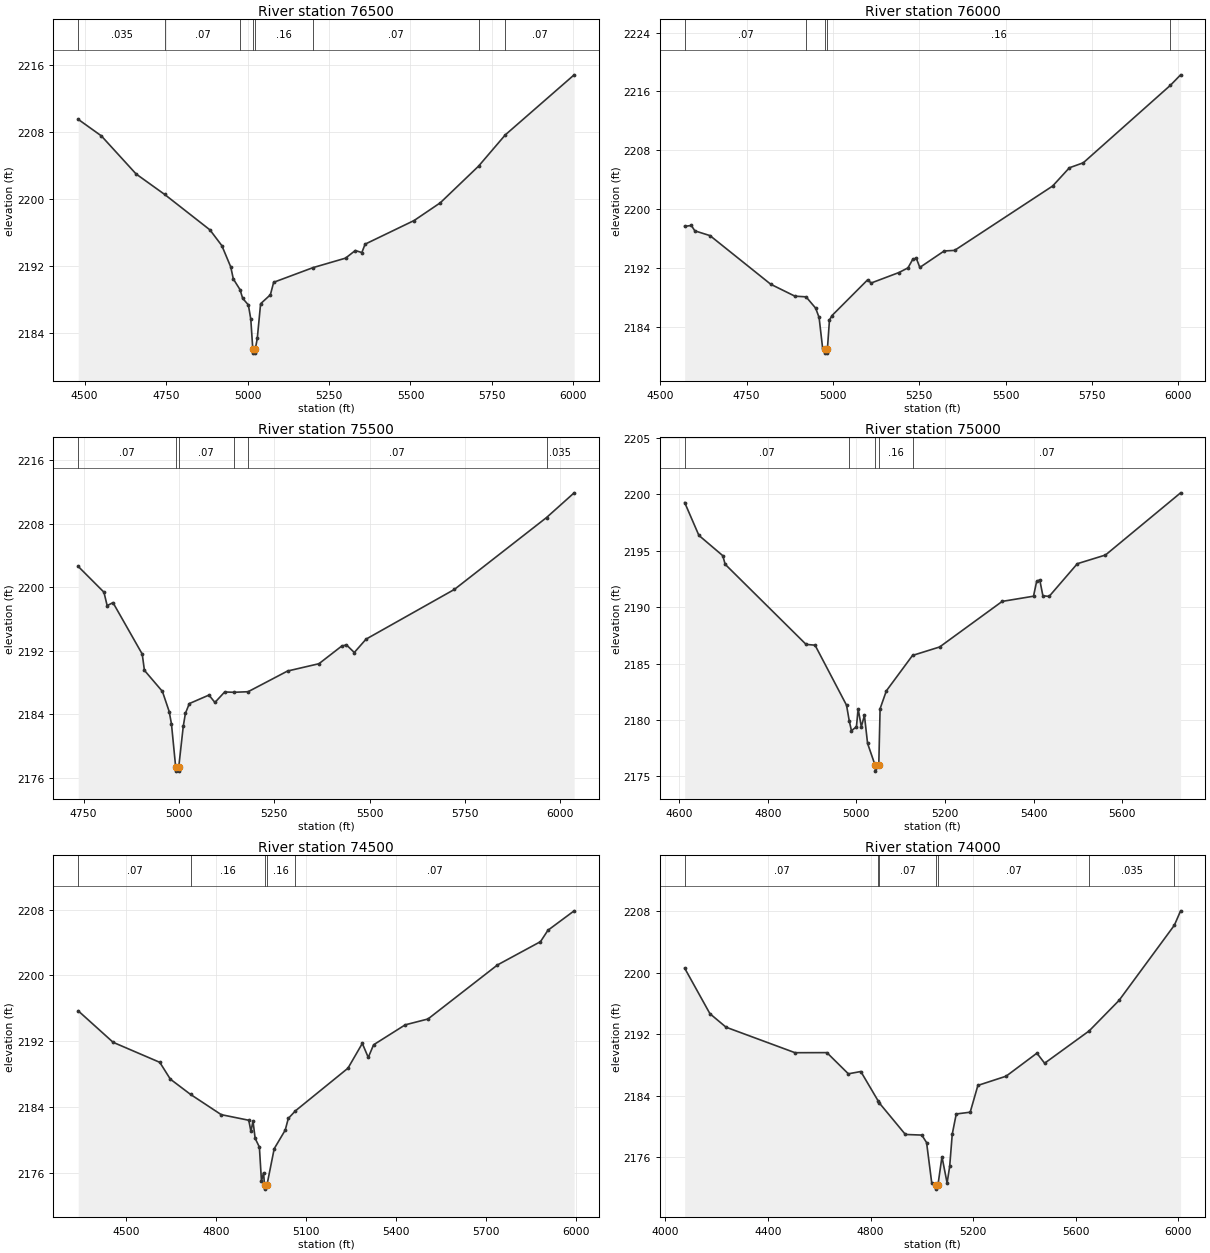
Type RM Length L Ch R = 1,76500,500,500,500
BEGIN DESCRIPTION:
Sweetwater Creek Trib 27 152.0
END DESCRIPTION:
XS GIS Cut Line= 3
      1356655.02      6877087.98      1356986.66      6876687.98
      1357055.00      6875688.01
#Sta/Elev= 30
  4480.4 2209.49  4551.3 2207.52  4658.1 2202.97  4745.7 2200.53  4884.7 2196.30
  4921.2 2194.42  4948.5 2191.88  4956.4 2190.45  4977.0 2189.17  4985.0 2188.14
  5002.5 2187.35  5010.0 2185.66  5016.1 2182.10  5016.6 2181.60  5023.5 2181.60
  5024.0 2182.10  5030.0 2183.39  5040.1 2187.49  5070.1 2188.56  5080.2 2190.05
  5200.9 2191.80  5300.7 2192.93  5330.7 2193.84  5350.8 2193.60  5360.8 2194.60
  5511.2 2197.42  5591.4 2199.53  5708.8 2203.90  5791.1 2207.64  6002.3 2214.80
#Mann=8,-1,0
  4480.4   0.035       0  4745.7    0.07       0  4977.0    0.16       0
  5016.1    0.07       0  5024.0    0.16       0  5200.9    0.07       0
  5708.8   0.035       0  5791.1    0.07       0
Bank Sta=5016.1,5024
Exp/Cntr=0.3,0.1

Type RM Length L Ch R = 1,76000,500,500,500
BEGIN DESCRIPTION:
Sweetwater Creek Trib 27 151.0
END DESCRIPTION:
XS GIS Cut Line= 3
      1357430.75      6877017.36      1357426.31      6876587.98
      1357305.00      6875588.01
#Sta/Elev= 30
  4570.6 2197.64  4590.0 2197.76  4600.0 2197.03  4644.0 2196.38  4820.0 2189.76
  4890.0 2188.14  4922.2 2188.05  4950.0 2186.51  4960.0 2185.24  4970.0 2181.15
  4976.0 2180.89  4976.5 2180.39  4983.5 2180.39  4984.0 2180.89  4990.0 2184.89
  4997.5 2185.51  5100.7 2190.37  5110.8 2189.93  5191.4 2191.36  5217.5 2191.99
  5231.7 2193.19  5241.7 2193.29  5251.8 2192.05  5322.3 2194.29  5352.5 2194.37
  5636.6 2203.13  5685.0 2205.61  5725.3 2206.29  5977.8 2216.84  6007.3 2218.26
#Mann=5,-1,0
  4570.6    0.07       0  4922.2    0.16       0  4976.0    0.07       0
  4984.0    0.16       0  5977.8   0.035       0
Bank Sta=4976,4984
Exp/Cntr=0.3,0.1

Type RM Length L Ch R = 1,75500,500,500,500
BEGIN DESCRIPTION:
Sweetwater Creek Trib 27 150.0
END DESCRIPTION:
XS GIS Cut Line= 3
      1357904.99      6876937.99      1357802.54      6876694.35
      1357555.01      6875688.05
#Sta/Elev= 30
  4735.7 2202.61  4803.2 2199.37  4811.6 2197.68  4826.9 2198.06  4903.6 2191.59
  4909.3 2189.55  4956.5 2186.90  4974.3 2184.37  4980.3 2182.79  4991.3 2177.38
  4991.8 2176.88  4998.8 2176.88  4999.3 2177.38  5011.2 2182.51  5016.8 2184.14
  5027.1 2185.37  5078.6 2186.44  5094.2 2185.51  5119.8 2186.83  5143.6 2186.79
  5181.2 2186.86  5284.6 2189.46  5367.0 2190.38  5426.5 2192.59  5439.1 2192.75
  5459.7 2191.79  5490.6 2193.47  5722.3 2199.72  5963.8 2208.75  6036.3 2211.86
#Mann=6,-1,0
  4735.7    0.07       0  4991.3    0.07       0  4999.3    0.07       0
  5143.6    0.16       0  5181.2    0.07       0  5963.8   0.035       0
Bank Sta=4991.3,4999.3
Exp/Cntr=0.3,0.1

Type RM Length L Ch R = 1,75000,500,500,500
BEGIN DESCRIPTION:
Sweetwater Creek Trib 27 149.0
END DESCRIPTION:
XS GIS Cut Line= 3
      1358105.01      6876887.95      1358172.67      6876506.00
      1357655.02      6875988.02
#Sta/Elev= 30
  4612.1 2199.27  4644.2 2196.36  4698.2 2194.56  4703.5 2193.80  4886.3 2186.70
  4906.6 2186.63  4977.7 2181.31  4983.8 2179.93  4988.8 2179.05  5000.0 2179.40
  5004.0 2180.97  5011.1 2179.40  5018.1 2180.41  5025.2 2177.93  5042.4 2175.97
  5042.9 2175.47  5050.5 2175.97  5053.5 2181.00  5067.6 2182.58  5126.7 2185.72
  5187.9 2186.47  5329.3 2190.51  5400.0 2190.97  5407.1 2192.28  5414.1 2192.42
  5421.2 2191.01  5435.3 2190.95  5499.0 2193.85  5562.6 2194.62  5732.3 2200.13
#Mann=5,-1,0
  4612.1    0.07       0  4983.8    0.16       0  5042.4    0.07       0
  5050.5    0.16       0  5126.7    0.07       0
Bank Sta=5042.4,5050.5
Exp/Cntr=0.3,0.1

Type RM Length L Ch R = 1,74500,500,500,500
BEGIN DESCRIPTION:
Sweetwater Creek Trib 27 148.0
END DESCRIPTION:
XS GIS Cut Line= 3
      1358156.97      6876864.59      1358613.64      6876387.67
      1358390.16      6875418.61
#Sta/Elev= 30
  4339.7 2195.70  4456.2 2191.88  4611.9 2189.45  4647.1 2187.41  4714.4 2185.56
  4816.9 2183.10  4908.8 2182.42  4916.0 2181.07  4922.9 2182.32  4930.1 2180.22
  4944.2 2179.17  4951.2 2175.02  4958.1 2176.05  4961.3 2174.56  4961.8 2174.06
  4969.5 2174.56  4993.7 2178.97  5030.4 2181.22  5040.7 2182.64  5064.4 2183.56
  5239.8 2188.74  5287.7 2191.75  5307.5 2190.04  5325.3 2191.58  5430.7 2194.00
  5506.7 2194.71  5738.6 2201.27  5882.2 2204.10  5907.0 2205.48  5994.5 2207.84
#Mann=5,-1,0
  4339.7    0.07       0  4714.4    0.16       0  4961.3    0.07       0
  4969.5    0.16       0  5064.4    0.07       0
Bank Sta=4961.3,4969.5
Exp/Cntr=0.3,0.1

Type RM Length L Ch R = 1,74000,382,382,382
BEGIN DESCRIPTION:
Sweetwater Creek Trib 27 147.0
END DESCRIPTION:
XS GIS Cut Line= 3
      1358105.02      6876937.99      1358964.60      6876596.57
      1359005.00      6875587.98
#Sta/Elev= 30
  4075.1 2200.59  4173.6 2194.66  4236.5 2192.90  4505.5 2189.58  4629.8 2189.59
  4713.5 2186.83  4762.1 2187.13  4830.6 2183.25  4833.8 2183.05  4935.9 2178.93
  5000.0 2178.85  5018.6 2177.87  5038.6 2172.64  5054.5 2172.31  5055.0 2171.81
  5062.8 2172.31  5078.6 2176.03  5098.6 2172.61  5108.7 2174.77  5118.7 2178.97
  5134.3 2181.60  5188.7 2181.83  5218.7 2185.32  5328.8 2186.52  5448.9 2189.52
  5479.0 2188.21  5652.7 2192.42  5769.2 2196.39  5984.9 2206.18  6009.4 2208.06
#Mann=7,-1,0
  4075.1    0.07       0  4830.6    0.16       0  4833.8    0.07       0
  5054.5    0.07       0  5062.8    0.07       0  5652.7   0.035       0
  5984.9    0.07       0
Bank Sta=5054.5,5062.8
Exp/Cntr=0.3,0.1

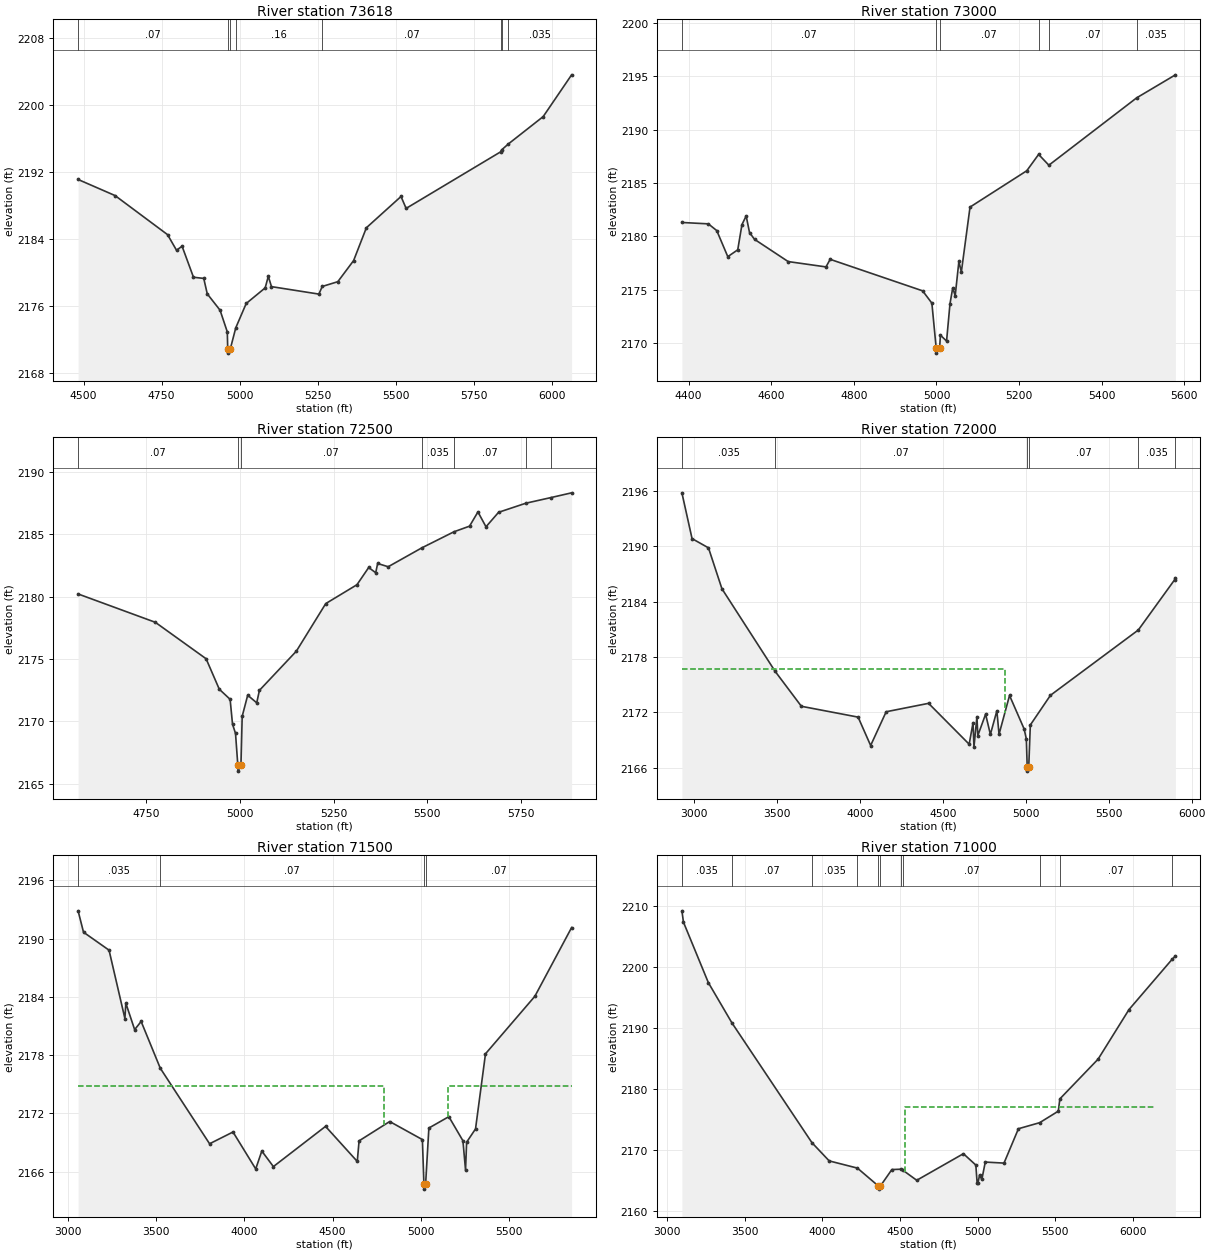
Type RM Length L Ch R = 1,73618,618,618,618
BEGIN DESCRIPTION:
Sweetwater Creek Trib 27 146.0
END DESCRIPTION:
XS GIS Cut Line= 3
      1358837.62      6876899.38      1359310.20      6876688.48
      1359150.59      6875638.04
#Sta/Elev= 30
  4482.5 2191.13  4600.9 2189.21  4768.9 2184.55  4797.6 2182.69  4815.4 2183.17
  4851.9 2179.47  4884.8 2179.33  4896.0 2177.49  4937.0 2175.54  4960.2 2172.95
  4961.5 2170.92  4962.0 2170.42  4969.8 2170.92  4987.4 2173.45  5020.7 2176.34
  5081.4 2178.20  5091.5 2179.58  5101.6 2178.35  5253.4 2177.46  5264.1 2178.37
  5314.0 2178.94  5364.6 2181.46  5405.4 2185.37  5516.3 2189.10  5532.7 2187.68
  5835.0 2194.42  5838.2 2194.65  5860.1 2195.37  5971.5 2198.63  6062.5 2203.61
#Mann=8,-1,0
  4482.5    0.07       0  4961.5    0.07       0  4969.8    0.07       0
  4987.4    0.16       0  5264.1    0.07       0  5835.0   0.035       0
  5838.2    0.07       0  5860.1   0.035       0
Bank Sta=4961.5,4969.8
Exp/Cntr=0.3,0.1

Type RM Length L Ch R = 1,73000,500,500,500
BEGIN DESCRIPTION:
Sweetwater Creek Trib 27 145.0
END DESCRIPTION:
XS GIS Cut Line= 3
      1359519.35      6876870.93      1359632.58      6876265.02
      1359304.98      6875787.98
#Sta/Elev= 30
  4383.6 2181.31  4447.6 2181.18  4468.0 2180.55  4494.7 2178.11  4518.8 2178.75
  4529.0 2181.11  4539.2 2181.92  4547.4 2180.36  4559.5 2179.73  4640.9 2177.65
  4732.5 2177.15  4742.6 2177.86  4966.5 2174.91  4988.9 2173.76  4999.3 2169.58
  4999.8 2169.08  5007.7 2169.58  5009.6 2170.76  5024.5 2170.21  5032.8 2173.71
  5039.4 2175.18  5045.4 2174.46  5054.3 2177.66  5060.3 2176.68  5081.3 2182.75
  5218.7 2186.15  5247.4 2187.68  5272.2 2186.67  5485.0 2192.98  5578.7 2195.13
#Mann=6,-1,0
  4383.6    0.07       0  4999.3    0.07       0  5007.7    0.07       0
  5247.4   0.035       0  5272.2    0.07       0  5485.0   0.035       0
Bank Sta=4999.3,5007.7
Exp/Cntr=0.3,0.1

Type RM Length L Ch R = 1,72500,500,500,500
BEGIN DESCRIPTION:
Sweetwater Creek Trib 27 144.0
END DESCRIPTION:
XS GIS Cut Line= 3
      1359663.38      6876805.89      1360001.99      6876538.11
      1359754.99      6875687.97
#Sta/Elev= 30
  4568.3 2180.21  4774.4 2177.94  4909.9 2175.02  4945.1 2172.58  4974.0 2171.77
  4980.4 2169.78  4988.4 2169.04  4994.5 2166.52  4995.0 2166.02  5002.9 2166.52
  5006.2 2170.41  5020.9 2172.10  5045.0 2171.49  5052.2 2172.49  5150.8 2175.63
  5229.2 2179.44  5312.5 2180.95  5343.8 2182.33  5362.5 2181.91  5367.7 2182.65
  5395.8 2182.39  5484.8 2183.89  5571.3 2185.19  5612.9 2185.64  5635.3 2186.78
  5656.8 2185.59  5690.4 2186.75  5763.4 2187.48  5830.2 2187.93  5885.3 2188.31
#Mann=7,-1,0
  4568.3    0.07       0  4994.5    0.07       0  5002.9    0.07       0
  5484.8   0.035       0  5571.3    0.07       0  5763.4   0.035       0
  5830.2    0.07       0
Bank Sta=4994.5,5002.9
Exp/Cntr=0.3,0.1

Type RM Length L Ch R = 1,72000,500,500,500
BEGIN DESCRIPTION:
Sweetwater Creek Trib 27 143.0
END DESCRIPTION:
XS GIS Cut Line= 3
      1361304.99      6878437.98      1360474.04      6876538.16
      1359905.02      6875838.03
#Sta/Elev= 30
  2926.4 2195.75  2987.6 2190.80  3086.6 2189.80  3167.7 2185.38  3488.5 2176.45
  3646.8 2172.67  3988.8 2171.50  4064.4 2168.43  4158.0 2172.08  4413.7 2172.99
  4658.5 2168.57  4681.9 2170.90  4687.4 2168.27  4705.3 2171.55  4710.8 2169.51
  4757.6 2171.82  4786.4 2169.63  4825.5 2172.18  4838.6 2169.64  4901.9 2173.84
  4989.9 2170.22  5003.2 2169.14  5008.3 2166.16  5008.8 2165.66  5017.8 2166.16
  5027.3 2170.65  5148.7 2173.86  5678.5 2180.92  5897.3 2186.35  5902.2 2186.55
#Mann=6,-1,0
  2926.4   0.035       0  3488.5    0.07       0  5008.3    0.07       0
  5017.8    0.07       0  5678.5   0.035       0  5897.3    0.07       0
#XS Ineff=2,0
    0.00 4873.60 2176.74               0
Permanent Ineff=
       F       F
Bank Sta=5008.3,5017.8
Exp/Cntr=0.3,0.1

Type RM Length L Ch R = 1,71500,500,500,500
BEGIN DESCRIPTION:
Sweetwater Creek Trib 27 142.0
END DESCRIPTION:
XS GIS Cut Line= 3
      1361305.00      6878388.02      1360909.89      6876485.31
      1361405.00      6875788.00
#Sta/Elev= 30
  3056.7 2192.86  3087.4 2190.66  3232.2 2188.81  3322.2 2181.77  3327.3 2183.36
  3377.4 2180.63  3414.2 2181.47  3522.7 2176.66  3802.3 2168.88  3935.1 2170.09
  4063.9 2166.29  4098.5 2168.13  4164.1 2166.53  4459.8 2170.67  4639.8 2167.06
  4650.0 2169.18  4823.6 2171.17  5009.0 2169.31  5017.7 2164.71  5018.2 2164.21
  5027.2 2164.71  5045.8 2170.50  5159.0 2171.67  5238.9 2169.19  5253.7 2166.17
  5259.8 2169.04  5310.3 2170.41  5366.8 2178.14  5646.7 2184.06  5855.2 2191.14
#Mann=4,-1,0
  3056.7   0.035       0  3522.7    0.07       0  5017.7    0.07       0
  5027.2    0.07       0
#XS Ineff=2,0
    0.00 4793.90 2174.84 5156.40    0.00 2174.84
Permanent Ineff=
       F       F
Bank Sta=5017.7,5027.2
Exp/Cntr=0.3,0.1

Type RM Length L Ch R = 1,71000,500,500,500
BEGIN DESCRIPTION:
Sweetwater Creek Trib 27 141.0
END DESCRIPTION:
XS GIS Cut Line= 3
      1361405.00      6878637.97      1361314.88      6876736.71
      1362105.02      6875737.97
#Sta/Elev= 30
  3096.6 2209.21  3106.6 2207.35  3266.8 2197.43  3418.5 2190.83  3933.7 2171.17
  4044.8 2168.18  4226.3 2167.00  4362.0 2164.05  4362.5 2163.55  4374.0 2164.05
  4448.1 2166.76  4508.6 2166.82  4521.3 2166.61  4608.3 2165.00  4908.6 2169.36
  4988.7 2167.50  4996.9 2164.59  5002.4 2164.59  5012.9 2165.85  5027.3 2165.13
  5049.4 2167.99  5170.0 2167.82  5262.9 2173.46  5399.4 2174.45  5519.4 2176.34
  5529.7 2178.36  5775.8 2184.88  5974.6 2193.01  6251.2 2201.23  6273.5 2201.80
#Mann=11,-1,0
  3096.6   0.035       0  3418.5    0.07       0  3933.7   0.035       0
  4226.3    0.07       0  4362.0    0.07       0  4374.0    0.07       0
  4508.6   0.035       0  4521.3    0.07       0  5399.4   0.063       0
  5529.7    0.07       0  6251.2   0.035       0
#XS Ineff=1,-1
 4535.00 6132.40 2177.00
Permanent Ineff=
       F
Bank Sta=4362,4374
Exp/Cntr=0.3,0.1

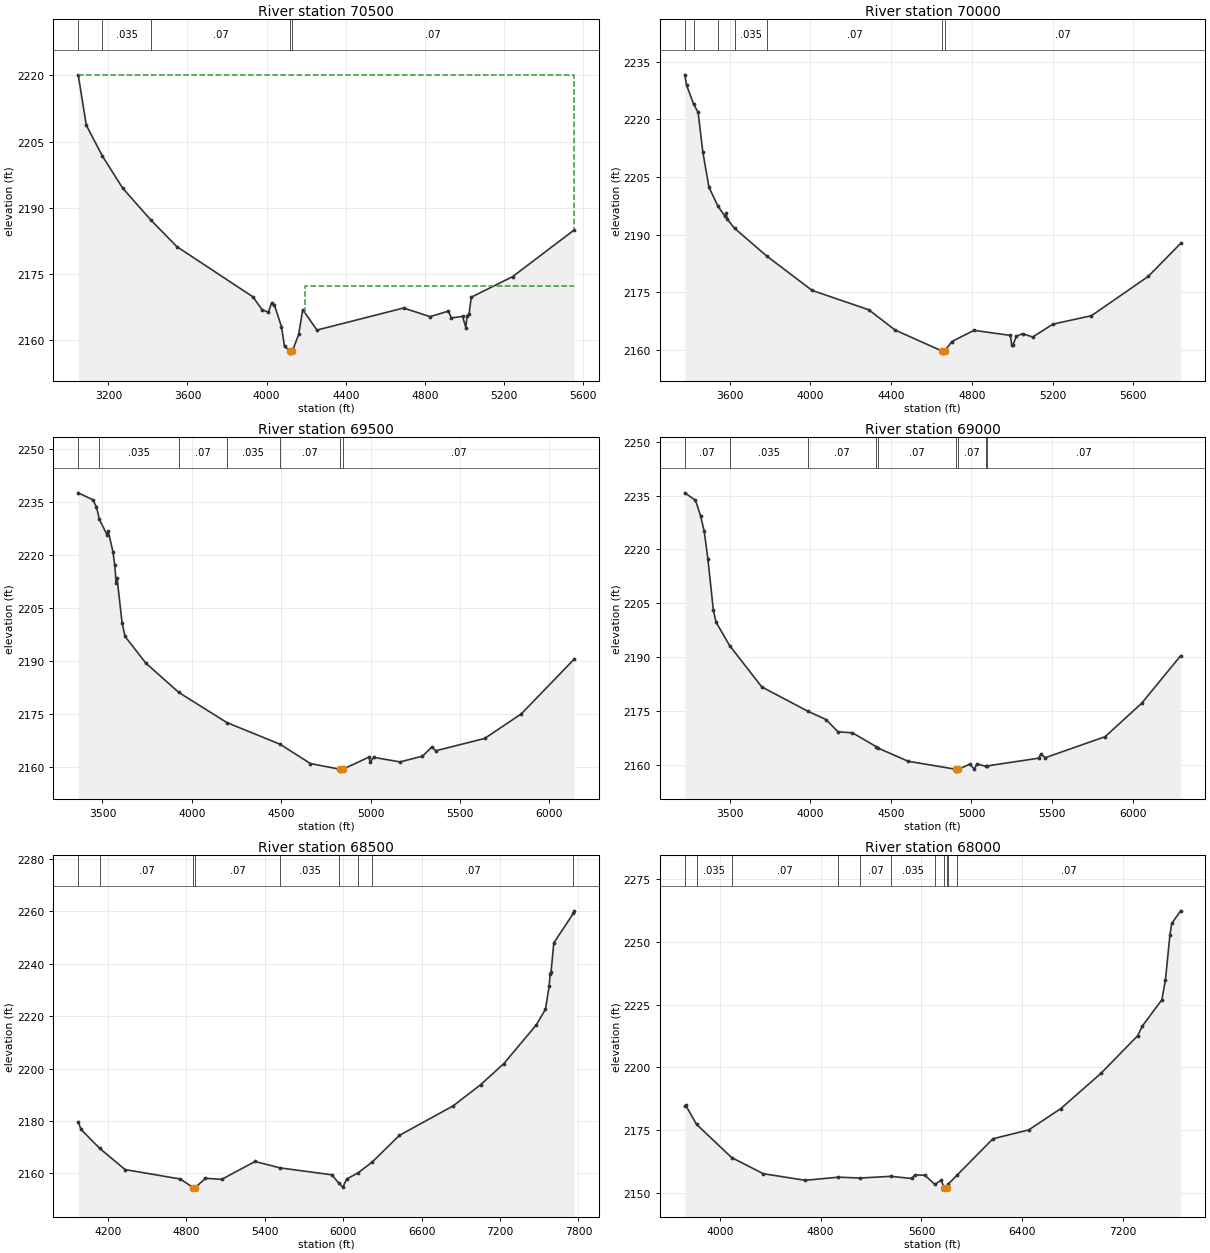
Type RM Length L Ch R = 1,70500,500,500,500
BEGIN DESCRIPTION:
Sweetwater Creek Trib 27 140.0
END DESCRIPTION:
XS GIS Cut Line= 3
      1362155.00      6878638.00      1361746.26      6876728.76
      1362005.01      6876237.99
#Sta/Elev= 30
  3047.5 2220.14  3088.4 2208.69  3170.2 2201.67  3272.5 2194.41  3416.0 2187.12
  3546.3 2181.14  3931.7 2169.72  3976.0 2166.86  4008.8 2166.24  4025.5 2168.41
  4039.5 2167.87  4074.9 2163.01  4090.6 2158.48  4118.4 2157.47  4118.9 2156.97
  4130.4 2157.47  4162.2 2161.23  4182.6 2166.87  4254.2 2162.20  4692.2 2167.21
  4826.9 2165.25  4919.0 2166.51  4934.3 2164.96  4990.5 2165.31  5007.3 2162.77
  5012.9 2165.40  5023.5 2165.86  5034.9 2169.67  5243.9 2174.34  5554.8 2184.92
#Mann=5,-1,0
  3047.5    0.07       0  3170.2   0.035       0  3416.0    0.07       0
  4118.4    0.07       0  4130.4    0.07       0
#XS Ineff=2,0
    0.00 3000.00 2220.00 4193.90    0.00 2172.22
Permanent Ineff=
       F       F
Bank Sta=4118.4,4130.4
Exp/Cntr=0.3,0.1

Type RM Length L Ch R = 1,70000,500,500,500
BEGIN DESCRIPTION:
Sweetwater Creek Trib 27 139.0
END DESCRIPTION:
XS GIS Cut Line= 3
      1362255.00      6878637.99      1362135.43      6877018.89
      1362055.00      6876187.98
#Sta/Elev= 30
  3376.5 2231.54  3386.5 2228.77  3420.3 2224.00  3443.0 2221.79  3466.7 2211.43
  3496.8 2202.37  3541.3 2197.42  3576.1 2194.81  3581.1 2195.62  3587.1 2194.05
  3624.0 2191.67  3782.4 2184.50  4008.2 2175.54  4289.0 2170.51  4419.3 2165.25
  4654.0 2159.75  4654.5 2159.25  4666.0 2159.75  4700.1 2162.24  4810.4 2165.16
  4990.9 2163.86  4997.9 2161.28  5003.0 2161.28  5021.0 2163.64  5051.1 2164.31
  5101.4 2163.43  5201.8 2166.78  5392.7 2168.97  5674.0 2179.16  5834.8 2187.75
#Mann=7,-1,0
  3376.5    0.07       0  3420.3   0.035       0  3541.3    0.07       0
  3624.0   0.035       0  3782.4    0.07       0  4654.0    0.07       0
  4666.0    0.07       0
Bank Sta=4654,4666
Exp/Cntr=0.3,0.1

Type RM Length L Ch R = 1,69500,500,500,500
BEGIN DESCRIPTION:
Sweetwater Creek Trib 27 138.0
END DESCRIPTION:
XS GIS Cut Line= 3
      1362255.01      6878737.95      1362597.61      6877138.43
      1362055.00      6876138.01
#Sta/Elev= 30
  3364.2 2237.58  3446.0 2235.61  3466.4 2233.60  3482.4 2230.05  3527.0 2225.57
  3532.1 2226.67  3558.5 2220.93  3568.7 2217.05  3576.4 2211.98  3581.5 2213.44
  3609.6 2200.84  3625.8 2197.00  3742.5 2189.44  3926.0 2181.18  4195.0 2172.64
  4493.4 2166.50  4663.0 2161.04  4830.8 2159.40  4831.3 2158.90  4842.8 2159.40
  4990.2 2162.86  4997.7 2161.50  5016.8 2162.79  5164.1 2161.51  5289.6 2163.13
  5341.8 2165.68  5364.5 2164.66  5637.6 2168.14  5842.3 2175.08  6138.1 2190.55
#Mann=7,-1,0
  3364.2    0.07       0  3482.4   0.035       0  3926.0    0.07       0
  4195.0   0.035       0  4493.4    0.07       0  4830.8    0.07       0
  4842.8    0.07       0
Bank Sta=4830.8,4842.8
Exp/Cntr=0.3,0.1

Type RM Length L Ch R = 1,69000,500,500,500
BEGIN DESCRIPTION:
Sweetwater Creek Trib 27 137.0
END DESCRIPTION:
XS GIS Cut Line= 3
      1362304.98      6878688.04      1363081.47      6877087.99
      1362255.01      6876088.02
#Sta/Elev= 30
  3221.5 2235.75  3288.2 2233.70  3320.3 2229.29  3342.9 2224.98  3365.5 2217.29
  3399.4 2203.04  3416.1 2199.69  3500.8 2193.14  3699.5 2181.65  3985.3 2174.87
  4098.7 2172.54  4172.0 2169.13  4262.3 2168.85  4409.9 2164.98  4421.2 2164.59
  4606.3 2160.94  4905.0 2158.67  4905.5 2158.17  4917.1 2158.67  4988.9 2160.09
  5018.7 2158.71  5033.1 2160.16  5088.3 2159.54  5096.8 2159.62  5416.0 2161.77
  5430.4 2162.88  5459.0 2161.93  5829.0 2167.77  6055.7 2177.08  6297.3 2190.33
#Mann=9,-1,0
  3221.5    0.07       0  3500.8   0.035       0  3985.3    0.07       0
  4409.9   0.035       0  4421.2    0.07       0  4905.0    0.07       0
  4917.1    0.07       0  5088.3   0.035       0  5096.8    0.07       0
Bank Sta=4905,4917.1
Exp/Cntr=0.3,0.1

Type RM Length L Ch R = 1,68500,500,500,500
BEGIN DESCRIPTION:
Sweetwater Creek Trib 27 136.0
END DESCRIPTION:
XS GIS Cut Line= 3
      1363154.99      6878138.03      1363544.16      6877188.92
      1365455.02      6875187.98
#Sta/Elev= 30
  3974.2 2179.68  3995.9 2176.77  4138.6 2169.56  4333.2 2161.47  4754.8 2157.89
  4855.5 2154.53  4856.0 2154.03  4867.6 2154.53  4947.0 2158.16  5071.9 2157.76
  5326.6 2164.56  5518.2 2162.12  5913.8 2159.49  5967.0 2156.29  5998.4 2154.79
  6026.7 2157.90  6112.1 2160.15  6223.5 2164.41  6429.9 2174.50  6840.3 2185.72
  7052.3 2193.85  7229.1 2201.87  7476.6 2216.57  7547.4 2222.56  7575.7 2231.42
  7582.9 2235.96  7589.9 2236.63  7611.2 2247.87  7761.4 2259.18  7766.8 2260.10
#Mann=9,-1,0
  3974.2   0.035       0  4138.6    0.07       0  4855.5    0.07       0
  4867.6    0.07       0  5518.2   0.035       0  5967.0    0.07       0
  6112.1   0.035       0  6223.5    0.07       0  7761.4   0.035       0
Bank Sta=4855.5,4867.6
Exp/Cntr=0.3,0.1

Type RM Length L Ch R = 1,68000,500,500,500
BEGIN DESCRIPTION:
Sweetwater Creek Trib 27 135.0
END DESCRIPTION:
XS GIS Cut Line= 3
      1363155.03      6878237.97      1364009.21      6877287.90
      1365755.01      6875287.99
#Sta/Elev= 30
  3722.4 2184.46  3729.5 2184.98  3816.7 2177.28  4094.3 2164.06  4345.4 2157.61
  4678.0 2154.97  4941.5 2156.22  5112.8 2155.88  5355.7 2156.55  5521.2 2155.71
  5549.7 2157.12  5627.5 2157.00  5705.1 2153.35  5755.7 2154.95  5781.5 2151.95
  5782.0 2151.45  5800.0 2151.95  5811.7 2153.43  5882.2 2157.03  6166.7 2171.55
  6449.6 2175.06  6704.9 2183.58  7023.9 2197.68  7314.4 2212.66  7349.5 2216.39
  7506.1 2226.99  7534.6 2235.04  7569.7 2252.73  7584.0 2257.42  7654.7 2262.47
#Mann=11,-1,0
  3722.4    0.07       0  3816.7   0.035       0  4094.3    0.07       0
  4941.5   0.035       0  5112.8    0.07       0  5355.7   0.035       0
  5705.1    0.07       0  5781.5   0.035       0  5800.0    0.07       0
  5811.7   0.035       0  5882.2    0.07       0
Bank Sta=5781.5,5800
Exp/Cntr=0.3,0.1