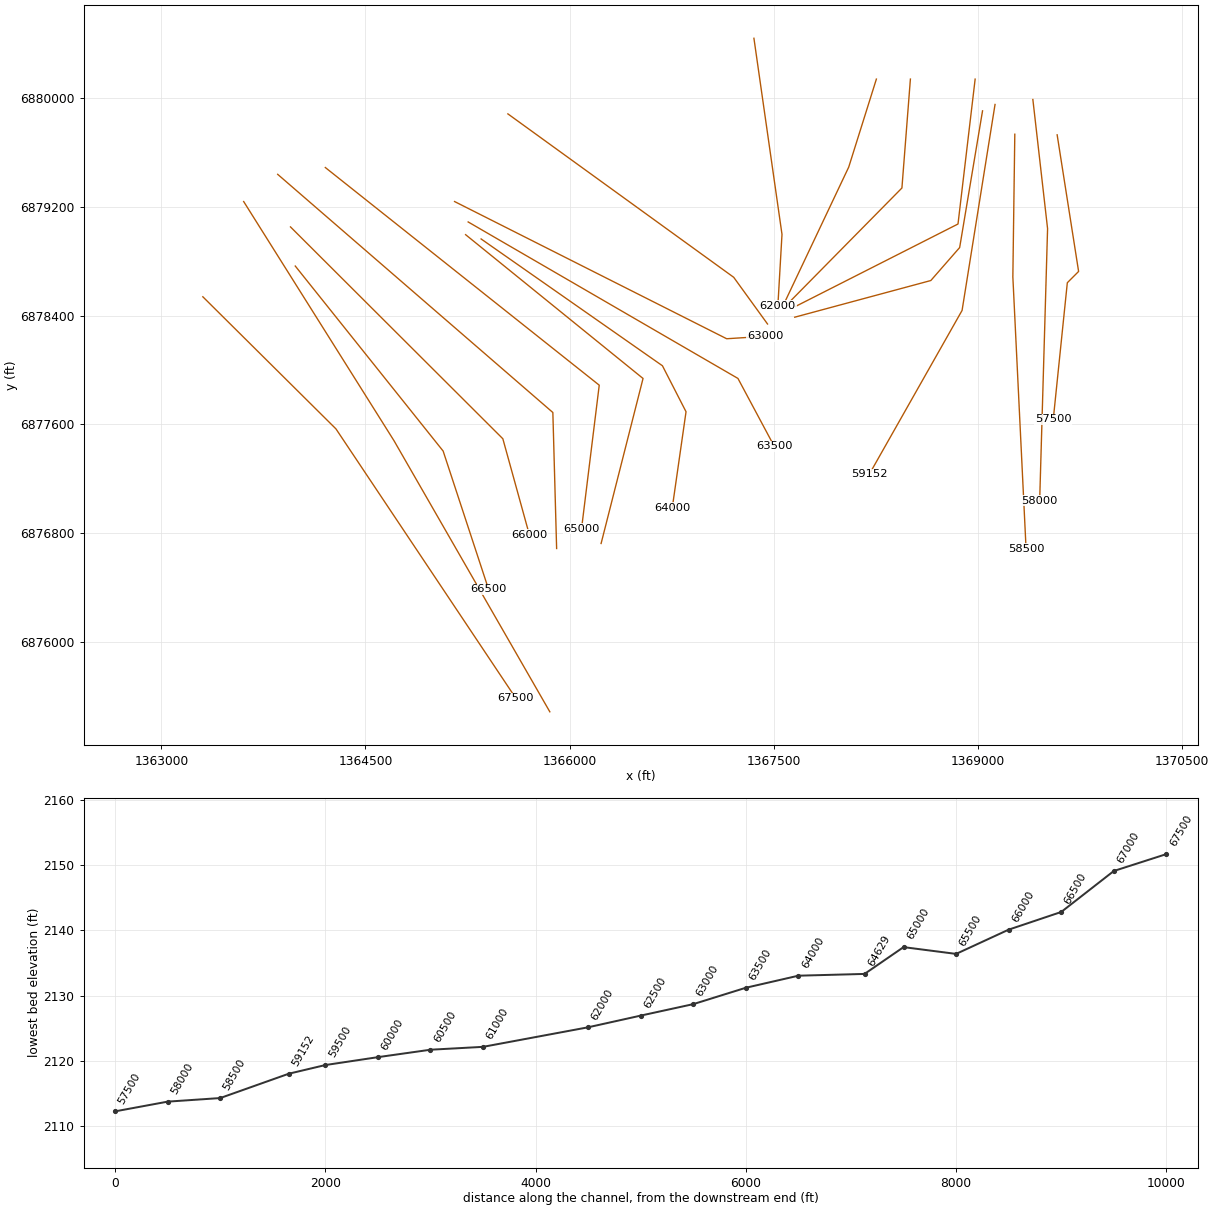
HEC-RAS study Sweetwater Creek Trib 27.prj: Sweetwater Creek Trib 27 Base Level Engineering

--- Sweetwater Creek Trib 27.g01 (geometry) --- (continued)

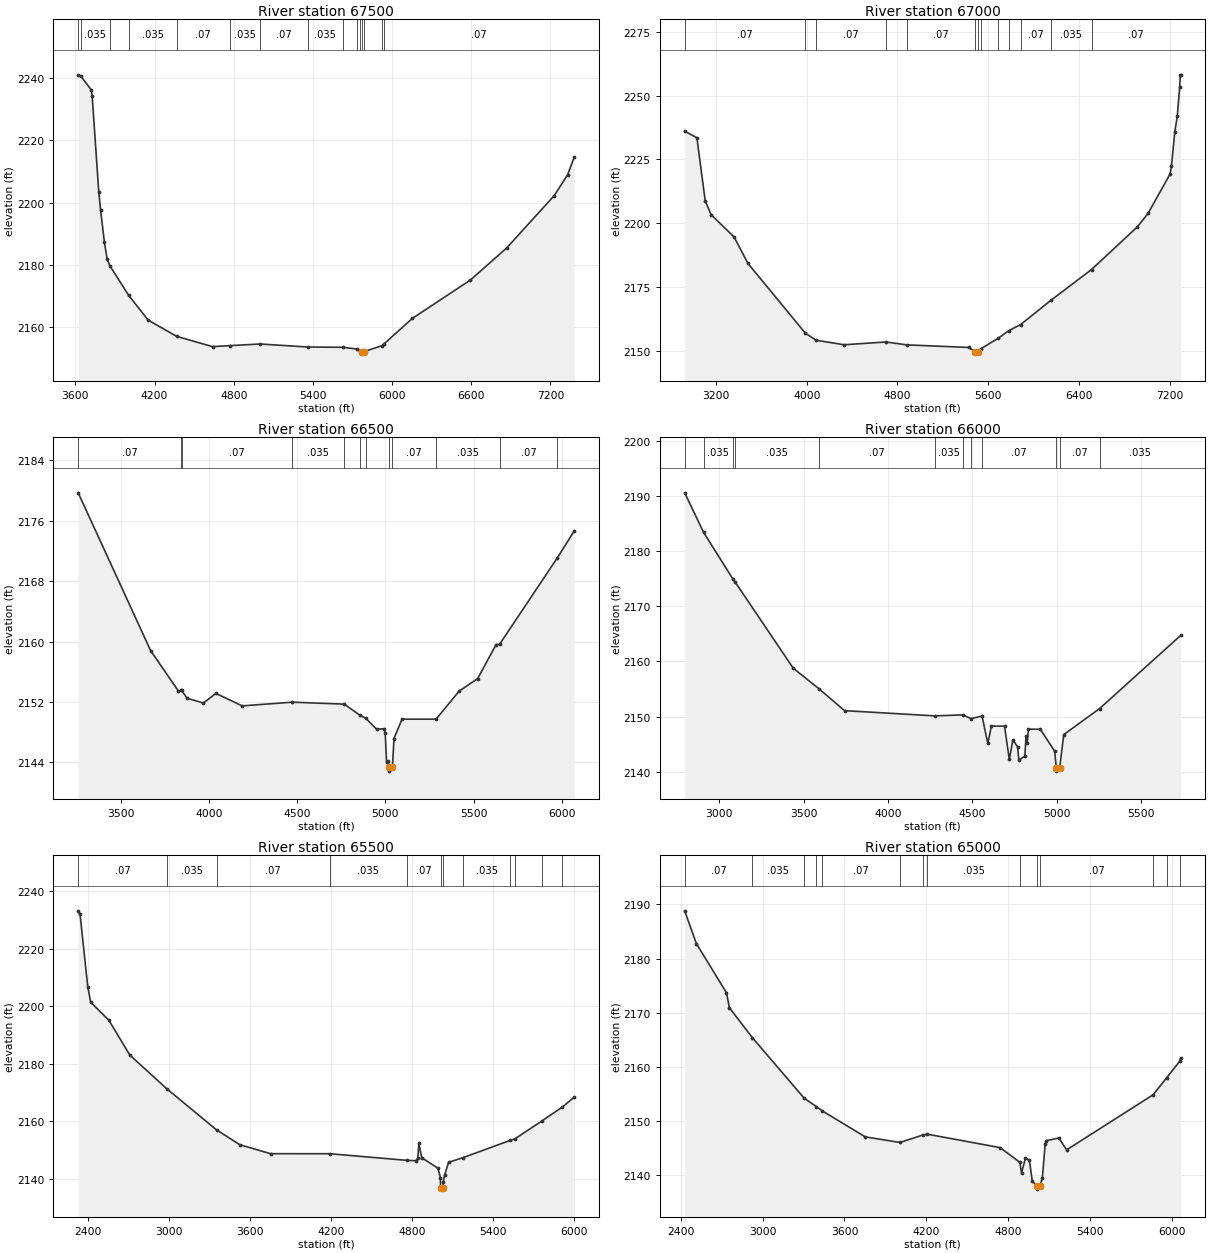
Type RM Length L Ch R = 1,67500,500,500,500
BEGIN DESCRIPTION:
Sweetwater Creek Trib 27 134.0
END DESCRIPTION:
XS GIS Cut Line= 3
      1363304.99      6878538.01      1364283.34      6877567.02
      1365605.02      6875587.98
#Sta/Elev= 30
  3621.6 2240.94  3641.1 2240.54  3720.6 2236.10  3727.7 2234.04  3777.2 2203.43
  3791.3 2197.53  3819.6 2187.39  3840.8 2181.91  3862.0 2179.68  4004.7 2170.19
  4152.0 2162.29  4366.8 2157.10  4639.8 2153.79  4770.2 2154.11  4999.2 2154.64
  5361.2 2153.67  5627.4 2153.58  5732.7 2153.03  5759.8 2152.27  5771.1 2152.21
  5771.6 2151.71  5789.6 2152.21  5922.9 2154.10  5936.2 2154.56  6153.2 2162.83
  6594.3 2175.17  6867.7 2185.41  7228.1 2202.17  7330.2 2208.89  7379.8 2214.47
#Mann=15,-1,0
  3621.6    0.07       0  3641.1   0.035       0  3862.0    0.07       0
  4004.7   0.035       0  4366.8    0.07       0  4770.2   0.035       0
  4999.2    0.07       0  5361.2   0.035       0  5627.4    0.07       0
  5732.7   0.035       0  5759.8    0.07       0  5771.1    0.07       0
  5789.6    0.07       0  5922.9   0.035       0  5936.2    0.07       0
Bank Sta=5771.1,5789.6
Exp/Cntr=0.3,0.1

Type RM Length L Ch R = 1,67000,500,500,500
BEGIN DESCRIPTION:
Sweetwater Creek Trib 27 133.0
END DESCRIPTION:
XS GIS Cut Line= 3
      1363605.01      6879237.99      1364709.93      6877480.22
      1365855.02      6875487.96
#Sta/Elev= 30
  2923.8 2236.09  3031.6 2233.54  3104.6 2208.90  3156.4 2203.40  3360.1 2194.62
  3481.5 2184.29  3987.3 2156.98  4082.3 2154.18  4329.5 2152.40  4698.7 2153.49
  4883.7 2152.35  5429.3 2151.35  5488.0 2149.62  5488.5 2149.12  5506.6 2149.62
  5538.1 2150.89  5690.4 2154.98  5782.5 2157.94  5886.7 2160.31  6154.8 2169.85
  6512.1 2181.88  6917.2 2198.64  7011.1 2203.90  7203.7 2219.22  7217.1 2222.37
  7246.8 2235.94  7268.4 2241.95  7290.0 2253.60  7295.0 2258.18  7297.9 2258.18
#Mann=13,-1,0
  2923.8    0.07       0  3987.3   0.035       0  4082.3    0.07       0
  4698.7   0.035       0  4883.7    0.07       0  5488.0    0.07       0
  5506.6    0.07       0  5538.1   0.035       0  5690.4    0.07       0
  5782.5   0.035       0  5886.7    0.07       0  6154.8   0.035       0
  6512.1    0.07       0
Bank Sta=5488,5506.6
Exp/Cntr=0.3,0.1

Type RM Length L Ch R = 1,66500,500,500,500
BEGIN DESCRIPTION:
Sweetwater Creek Trib 27 132.0
END DESCRIPTION:
XS GIS Cut Line= 3
      1363984.27      6878763.88      1365071.02      6877404.22
      1365405.00      6876388.00
#Sta/Elev= 30
  3259.4 2179.69  3669.6 2158.80  3826.5 2153.47  3843.8 2153.52  3845.1 2153.53
  3876.1 2152.49  3969.0 2151.86  4039.4 2153.13  4188.7 2151.48  4472.5 2151.97
  4766.8 2151.71  4854.6 2150.26  4889.4 2149.83  4950.3 2148.38  4993.6 2148.46
  4999.2 2147.84  5006.5 2144.10  5017.1 2144.20  5021.5 2143.34  5022.0 2142.84
  5040.1 2143.34  5048.7 2147.16  5094.4 2149.72  5287.3 2149.72  5417.7 2153.43
  5522.3 2155.08  5627.6 2159.60  5646.9 2159.63  5975.0 2171.10  6069.7 2174.63
#Mann=12,-1,0
  3259.4    0.07       0  3843.8   0.035       0  3845.1    0.07       0
  4472.5   0.035       0  4766.8    0.07       0  4854.6   0.035       0
  4889.4    0.07       0  5021.5    0.07       0  5040.1    0.07       0
  5287.3   0.035       0  5646.9    0.07       0  5975.0   0.035       0
Bank Sta=5021.5,5040.1
Exp/Cntr=0.3,0.1

Type RM Length L Ch R = 1,66000,500,500,500
BEGIN DESCRIPTION:
Sweetwater Creek Trib 27 131.0
END DESCRIPTION:
XS GIS Cut Line= 3
      1363949.15      6879051.48      1365509.73      6877494.57
      1365705.01      6876787.96
#Sta/Elev= 30
  2795.6 2190.55  2907.9 2183.37  3082.9 2174.85  3094.4 2174.39  3438.6 2158.78
  3591.3 2155.05  3742.6 2151.09  4277.8 2150.14  4442.5 2150.32  4492.1 2149.65
  4556.9 2150.11  4591.2 2145.14  4612.4 2148.30  4690.2 2148.27  4718.5 2142.24
  4739.7 2145.83  4767.9 2144.49  4775.0 2142.14  4810.4 2142.84  4817.5 2146.46
  4824.5 2145.21  4831.6 2147.74  4902.3 2147.71  4987.2 2143.73  4997.3 2140.63
  4997.8 2140.13  5016.4 2140.63  5040.8 2146.75  5253.5 2151.47  5733.1 2164.71
#Mann=12,-1,0
  2795.6    0.07       0  2907.9   0.035       0  3082.9    0.07       0
  3094.4   0.035       0  3591.3    0.07       0  4277.8   0.035       0
  4442.5    0.07       0  4492.1   0.035       0  4556.9    0.07       0
  4997.3    0.07       0  5016.4    0.07       0  5253.5   0.035       0
Bank Sta=4997.3,5016.4
Exp/Cntr=0.3,0.1

Type RM Length L Ch R = 1,65500,500,500,500
BEGIN DESCRIPTION:
Sweetwater Creek Trib 27 130.0
END DESCRIPTION:
XS GIS Cut Line= 3
      1363855.02      6879437.98      1365877.30      6877687.59
      1365905.00      6876687.97
#Sta/Elev= 30
  2325.4 2233.21  2339.1 2232.04  2396.1 2206.79  2418.0 2201.41  2551.9 2195.20
  2708.7 2182.99  2980.0 2171.39  3350.7 2157.00  3523.6 2151.85  3750.6 2148.74
  4188.1 2148.73  4758.5 2146.43  4827.6 2146.29  4841.9 2147.24  4849.5 2152.37
  4870.4 2147.33  4991.0 2143.69  5009.6 2140.33  5010.0 2136.91  5010.5 2136.41
  5029.1 2136.91  5029.6 2138.89  5039.6 2141.24  5069.6 2145.73  5178.3 2147.40
  5527.9 2153.39  5561.3 2153.90  5759.9 2160.09  5912.2 2164.95  6000.0 2168.37
#Mann=12,-1,0
  2325.4    0.07       0  2980.0   0.035       0  3350.7    0.07       0
  4188.1   0.035       0  4758.5    0.07       0  5010.0    0.07       0
  5029.1    0.07       0  5178.3   0.035       0  5527.9    0.07       0
  5561.3   0.035       0  5759.9    0.07       0  5912.2   0.035       0
Bank Sta=5010,5029.1
Exp/Cntr=0.3,0.1

Type RM Length L Ch R = 1,65000,371,371,371
BEGIN DESCRIPTION:
Sweetwater Creek Trib 27 129.0
END DESCRIPTION:
XS GIS Cut Line= 3
      1364205.03      6879487.98      1366218.19      6877888.36
      1366087.94      6876832.17
#Sta/Elev= 30
  2428.7 2188.81  2514.4 2182.76  2735.2 2173.69  2756.3 2170.93  2924.4 2165.42
  3305.8 2154.20  3394.1 2152.69  3438.6 2151.87  3752.7 2147.09  4007.4 2146.06
  4175.7 2147.45  4207.7 2147.59  4741.1 2145.11  4885.2 2142.42  4898.1 2140.45
  4927.0 2143.21  4955.8 2142.76  4976.6 2138.97  5010.9 2137.95  5011.4 2137.45
  5030.1 2137.95  5050.7 2139.50  5071.4 2145.83  5081.0 2146.41  5171.7 2146.88
  5228.7 2144.70  5863.0 2154.87  5962.0 2158.00  6056.7 2161.02  6064.2 2161.64
#Mann=14,-1,0
  2428.7    0.07       0  2924.4   0.035       0  3305.8    0.07       0
  3394.1   0.035       0  3438.6    0.07       0  4007.4   0.035       0
  4175.7    0.07       0  4207.7   0.035       0  4885.2    0.07       0
  5010.9    0.07       0  5030.1    0.07       0  5863.0   0.035       0
  5962.0    0.07       0  6056.7   0.035       0
Bank Sta=5010.9,5030.1
Exp/Cntr=0.3,0.1

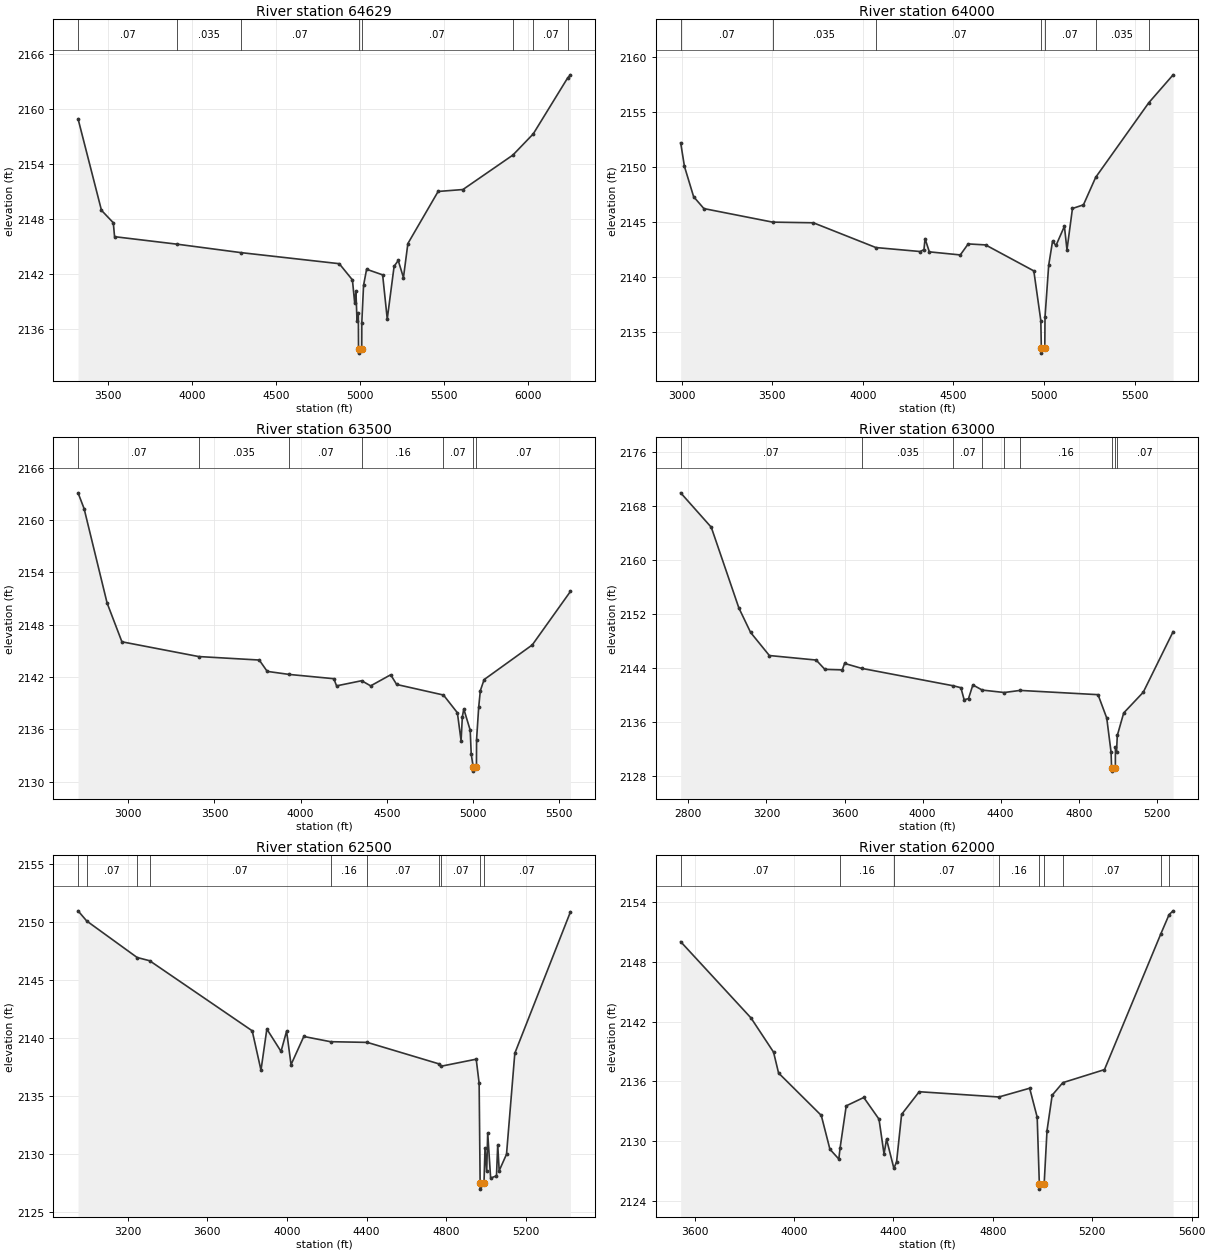
Type RM Length L Ch R = 1,64629,629,629,629
BEGIN DESCRIPTION:
Sweetwater Creek Trib 27 128.0
END DESCRIPTION:
XS GIS Cut Line= 3
      1365236.18      6878994.42      1366540.11      6877937.64
      1366231.84      6876724.80
#Sta/Elev= 30
  3321.6 2158.94  3461.0 2148.94  3531.4 2147.58  3538.9 2146.06  3911.3 2145.24
  4290.3 2144.32  4875.7 2143.11  4954.0 2141.34  4967.7 2138.79  4974.9 2140.10
  4981.3 2136.86  4989.2 2137.75  4990.3 2133.84  4990.8 2133.34  5009.5 2133.84
  5009.9 2136.68  5020.3 2140.75  5038.4 2142.50  5133.8 2141.89  5161.2 2137.07
  5202.1 2142.83  5226.6 2143.46  5257.6 2141.59  5284.0 2145.31  5463.9 2151.00
  5611.5 2151.21  5908.4 2154.97  6029.9 2157.29  6234.1 2163.39  6251.4 2163.74
#Mann=8,-1,0
  3321.6    0.07       0  3911.3   0.035       0  4290.3    0.07       0
  4990.3    0.07       0  5009.5    0.07       0  5908.4   0.035       0
  6029.9    0.07       0  6234.1   0.035       0
Bank Sta=4990.3,5009.5
Exp/Cntr=0.3,0.1

Type RM Length L Ch R = 1,64000,500,500,500
BEGIN DESCRIPTION:
Sweetwater Creek Trib 27 127.0
END DESCRIPTION:
XS GIS Cut Line= 4
      1365350.01      6878962.99      1366682.63      6878031.07
      1366856.06      6877693.23      1366755.00      6876988.03
#Sta/Elev= 30
  2994.1 2152.18  3015.0 2150.03  3065.6 2147.28  3122.3 2146.20  3501.6 2144.97
  3726.6 2144.91  4071.7 2142.66  4316.1 2142.30  4337.0 2142.47  4343.1 2143.47
  4366.7 2142.27  4537.7 2141.99  4581.2 2142.99  4677.2 2142.90  4943.5 2140.54
  4982.2 2136.02  4984.9 2133.57  4985.4 2133.07  5004.1 2133.57  5005.3 2136.34
  5025.5 2141.04  5046.7 2143.22  5065.9 2142.85  5112.3 2144.59  5126.5 2142.46
  5156.8 2146.21  5217.4 2146.54  5285.0 2149.04  5577.9 2155.81  5712.4 2158.35
#Mann=7,-1,0
  2994.1    0.07       0  3501.6   0.035       0  4071.7    0.07       0
  4984.9    0.07       0  5004.1    0.07       0  5285.0   0.035       0
  5577.9    0.07       0
Bank Sta=4984.9,5004.1
Exp/Cntr=0.3,0.1

Type RM Length L Ch R = 1,63500,500,500,500
BEGIN DESCRIPTION:
Sweetwater Creek Trib 27 126.0
END DESCRIPTION:
XS GIS Cut Line= 3
      1365254.96      6879088.02      1367237.61      6877937.88
      1367505.00      6877438.00
#Sta/Elev= 30
  2707.9 2163.11  2743.1 2161.30  2876.5 2150.49  2962.6 2146.04  3407.9 2144.35
  3760.0 2143.95  3806.2 2142.65  3933.8 2142.30  4193.1 2141.81  4208.8 2140.99
  4354.5 2141.58  4406.7 2140.99  4523.0 2142.26  4557.7 2141.15  4829.5 2139.94
  4910.2 2137.91  4931.7 2134.71  4939.2 2137.47  4947.4 2138.34  4984.7 2135.91
  4990.5 2133.22  5001.6 2131.72  5002.1 2131.22  5020.9 2131.72  5021.6 2134.81
  5033.9 2138.53  5043.5 2140.44  5065.5 2141.71  5345.0 2145.68  5566.9 2151.82
#Mann=7,-1,0
  2707.9    0.07       0  3407.9   0.035       0  3933.8    0.07       0
  4354.5    0.16       0  4829.5    0.07       0  5001.6    0.07       0
  5020.9    0.07       0
Bank Sta=5001.6,5020.9
Exp/Cntr=0.3,0.1

Type RM Length L Ch R = 1,63000,500,500,500
BEGIN DESCRIPTION:
Sweetwater Creek Trib 27 125.0
END DESCRIPTION:
XS GIS Cut Line= 3
      1365155.02      6879237.99      1367154.77      6878229.63
      1367437.70      6878247.66
#Sta/Elev= 30
  2760.4 2169.95  2917.2 2164.85  3058.7 2152.88  3118.8 2149.26  3214.8 2145.84
  3454.6 2145.17  3499.2 2143.79  3588.4 2143.71  3600.3 2144.67  3687.5 2143.94
  4158.1 2141.35  4196.2 2141.07  4212.9 2139.28  4235.2 2139.46  4257.5 2141.48
  4305.7 2140.72  4418.3 2140.36  4499.6 2140.67  4898.8 2140.04  4943.4 2136.58
  4965.7 2131.50  4968.2 2129.21  4968.7 2128.71  4987.5 2129.21  4988.0 2132.24
  4993.6 2131.56  4997.5 2133.99  5030.3 2137.33  5130.5 2140.40  5283.5 2149.38
#Mann=9,-1,0
  2760.4    0.07       0  3687.5   0.035       0  4158.1    0.07       0
  4305.7    0.16       0  4418.3    0.07       0  4499.6    0.16       0
  4968.2    0.07       0  4987.5    0.16       0  4997.5    0.07       0
Bank Sta=4968.2,4987.5
Exp/Cntr=0.3,0.1

Type RM Length L Ch R = 1,62500,500,500,500
BEGIN DESCRIPTION:
Sweetwater Creek Trib 27 124.0
END DESCRIPTION:
XS GIS Cut Line= 3
      1365546.80      6879882.17      1367206.38      6878681.27
      1367454.97      6878338.04
#Sta/Elev= 30
  2951.5 2150.98  2995.3 2150.10  3248.2 2146.95  3311.1 2146.67  3825.9 2140.62
  3870.0 2137.22  3899.4 2140.77  3970.6 2138.84  3998.5 2140.59  4020.9 2137.70
  4084.9 2140.13  4219.1 2139.68  4403.7 2139.62  4764.6 2137.76  4773.5 2137.56
  4950.5 2138.17  4965.2 2136.09  4970.2 2127.45  4970.7 2126.95  4989.5 2127.45
  4994.6 2130.46  5003.1 2128.48  5008.2 2131.80  5022.9 2127.90  5052.3 2128.10
  5058.5 2130.79  5065.8 2128.54  5102.6 2129.96  5144.3 2138.68  5423.8 2150.90
#Mann=10,-1,0
  2951.5   0.035       0  2995.3    0.07       0  3248.2   0.035       0
  3311.1    0.07       0  4219.1    0.16       0  4403.7    0.07       0
  4764.6    0.16       0  4773.5    0.07       0  4970.2    0.07       0
  4989.5    0.07       0
Bank Sta=4970.2,4989.5
Exp/Cntr=0.3,0.1

Type RM Length L Ch R = 1,62000,1000,1000,1000
BEGIN DESCRIPTION:
Sweetwater Creek Trib 27 123.0
END DESCRIPTION:
XS GIS Cut Line= 3
      1367355.00      6880437.97      1367561.29      6878996.76
      1367531.00      6878472.24
#Sta/Elev= 30
  3544.1 2150.03  3826.9 2142.37  3917.8 2138.93  3938.0 2136.83  4109.8 2132.57
  4144.6 2129.17  4180.5 2128.18  4185.4 2129.28  4210.2 2133.53  4280.8 2134.37
  4342.1 2132.19  4362.3 2128.69  4372.4 2130.18  4401.9 2127.25  4412.8 2127.90
  4433.0 2132.67  4503.8 2134.95  4824.4 2134.42  4948.2 2135.30  4978.5 2132.39
  4987.2 2125.66  4987.7 2125.16  5006.5 2125.66  5018.0 2131.03  5038.8 2134.60
  5081.6 2135.86  5249.2 2137.17  5475.2 2150.77  5509.2 2152.75  5525.4 2153.13
#Mann=9,-1,0
  3544.1    0.07       0  4185.4    0.16       0  4401.9    0.07       0
  4824.4    0.16       0  4987.2    0.07       0  5006.5    0.16       0
  5081.6    0.07       0  5475.2   0.035       0  5509.2    0.07       0
Bank Sta=4987.2,5006.5
Exp/Cntr=0.3,0.1

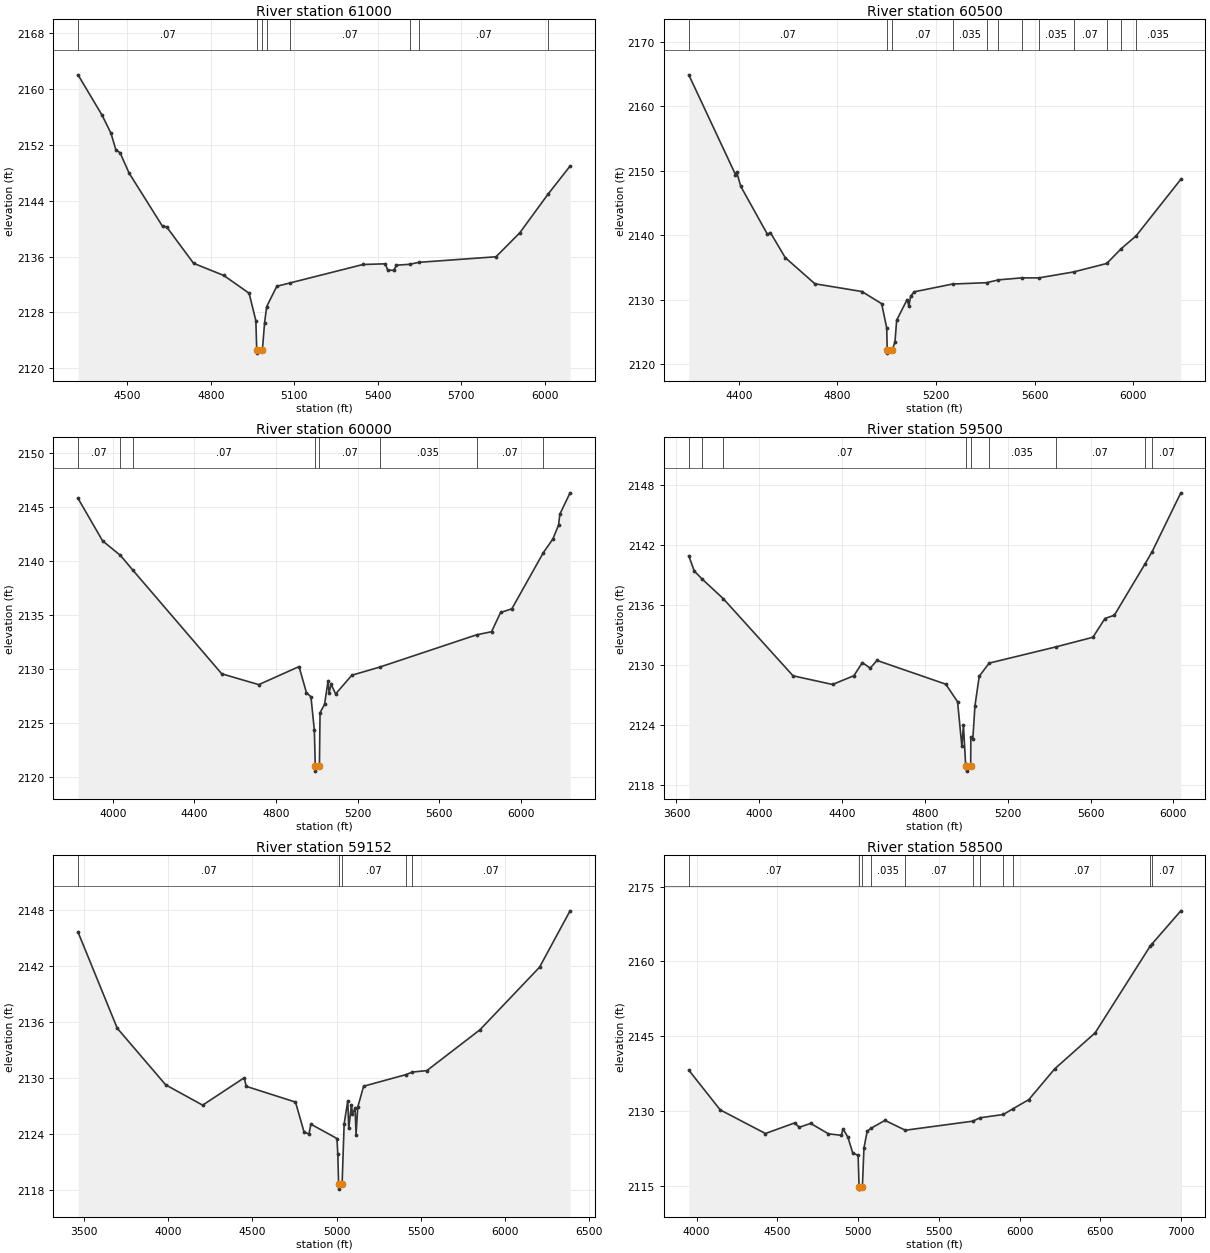
Type RM Length L Ch R = 1,61000,500,500,500
BEGIN DESCRIPTION:
Sweetwater Creek Trib 27 121.0
END DESCRIPTION:
XS GIS Cut Line= 3
      1368254.99      6880137.96      1368051.81      6879491.32
      1367584.77      6878505.13
#Sta/Elev= 30
  4322.2 2162.07  4408.4 2156.30  4440.8 2153.69  4458.4 2151.30  4473.2 2150.91
  4505.6 2148.00  4626.1 2140.34  4640.5 2140.28  4737.7 2135.04  4846.3 2133.30
  4937.3 2130.75  4961.6 2126.81  4964.7 2122.66  4965.2 2122.16  4985.2 2122.66
  4993.0 2126.55  5000.6 2128.84  5036.9 2131.75  5084.9 2132.23  5346.7 2134.87
  5427.2 2134.97  5435.2 2134.09  5457.3 2134.02  5467.2 2134.77  5514.7 2134.90
  5547.9 2135.18  5825.0 2135.98  5910.4 2139.41  6011.1 2144.91  6091.2 2148.98
#Mann=8,-1,0
  4322.2    0.07       0  4964.7    0.07       0  4985.2    0.07       0
  5000.6    0.16       0  5084.9    0.07       0  5514.7   0.035       0
  5547.9    0.07       0  6011.1   0.035       0
Bank Sta=4964.7,4985.2
Exp/Cntr=0.3,0.1

Type RM Length L Ch R = 1,60500,500,500,500
BEGIN DESCRIPTION:
Sweetwater Creek Trib 27 120.0
END DESCRIPTION:
XS GIS Cut Line= 3
      1368505.00      6880138.04      1368442.63      6879337.47
      1367604.99      6878487.99
#Sta/Elev= 30
  4197.0 2164.90  4386.4 2149.43  4391.4 2149.81  4407.7 2147.61  4516.0 2140.16
  4528.0 2140.43  4588.2 2136.54  4708.6 2132.48  4899.2 2131.28  4979.4 2129.39
  5000.0 2125.62  5001.9 2122.22  5002.4 2121.72  5022.4 2122.22  5033.3 2123.42
  5040.4 2126.84  5082.9 2130.04  5089.9 2129.00  5097.0 2130.54  5111.1 2131.23
  5267.0 2132.44  5405.4 2132.65  5453.4 2133.09  5549.7 2133.40  5616.6 2133.39
  5758.4 2134.32  5892.5 2135.63  5951.8 2137.95  6011.3 2139.90  6193.0 2148.69
#Mann=12,-1,0
  4197.0    0.07       0  5001.9    0.07       0  5022.4    0.07       0
  5267.0   0.035       0  5405.4    0.07       0  5453.4   0.035       0
  5549.7    0.07       0  5616.6   0.035       0  5758.4    0.07       0
  5892.5   0.035       0  5951.8    0.07       0  6011.3   0.035       0
Bank Sta=5001.9,5022.4
Exp/Cntr=0.3,0.1

Type RM Length L Ch R = 1,60000,500,500,500
BEGIN DESCRIPTION:
Sweetwater Creek Trib 27 119.0
END DESCRIPTION:
XS GIS Cut Line= 3
      1368980.81      6880137.63      1368854.83      6879072.90
      1367660.61      6878466.95
#Sta/Elev= 30
  3829.2 2145.84  3949.7 2141.90  4036.8 2140.56  4099.3 2139.16  4533.7 2129.59
  4715.0 2128.59  4912.4 2130.26  4948.5 2127.85  4970.7 2127.46  4987.4 2124.37
  4991.8 2121.08  4992.3 2120.58  5012.3 2121.08  5015.3 2125.99  5037.5 2126.77
  5054.2 2128.88  5059.8 2127.84  5069.4 2128.62  5091.8 2127.73  5171.1 2129.46
  5310.5 2130.23  5782.1 2133.20  5855.7 2133.49  5900.2 2135.27  5955.2 2135.61
  6109.9 2140.82  6156.2 2142.07  6184.0 2143.36  6190.7 2144.38  6240.5 2146.35
#Mann=8,-1,0
  3829.2    0.07       0  4036.8   0.035       0  4099.3    0.07       0
  4991.8    0.07       0  5012.3    0.07       0  5310.5   0.035       0
  5782.1    0.07       0  6109.9   0.035       0
Bank Sta=4991.8,5012.3
Exp/Cntr=0.3,0.1

Type RM Length L Ch R = 1,59500,348,348,348
BEGIN DESCRIPTION:
Sweetwater Creek Trib 27 118.0
END DESCRIPTION:
XS GIS Cut Line= 4
      1369035.17      6879904.59      1368867.00      6878899.84
      1368655.17      6878657.50      1367655.04      6878388.01
#Sta/Elev= 30
  3659.4 2140.94  3686.0 2139.41  3725.1 2138.59  3825.9 2136.65  4162.9 2128.92
  4353.8 2128.05  4456.9 2128.93  4497.5 2130.24  4535.9 2129.69  4568.5 2130.46
  4900.6 2128.08  4957.6 2126.32  4978.4 2121.85  4986.0 2123.96  4996.3 2120.10
  5000.3 2119.87  5000.8 2119.37  5020.8 2119.87  5021.7 2122.81  5031.2 2122.59
  5041.6 2125.93  5062.3 2128.88  5110.1 2130.19  5431.3 2131.81  5611.2 2132.78
  5669.4 2134.66  5714.8 2134.99  5862.4 2140.11  5897.6 2141.37  6035.8 2147.25
#Mann=9,-1,0
  3659.4    0.07       0  3725.1   0.035       0  3825.9    0.07       0
  5000.3    0.07       0  5020.8    0.07       0  5110.1   0.035       0
  5431.3    0.07       0  5862.4   0.035       0  5897.6    0.07       0
Bank Sta=5000.3,5020.8
Exp/Cntr=0.3,0.1

Type RM Length L Ch R = 1,59152,652,652,652
BEGIN DESCRIPTION:
Sweetwater Creek Trib 27 117.0
END DESCRIPTION:
XS GIS Cut Line= 3
      1369126.99      6879951.36      1368884.79      6878437.72
      1368202.39      6877232.84
#Sta/Elev= 30
  3467.1 2145.62  3699.8 2135.30  3987.0 2129.23  4206.1 2127.05  4452.8 2129.99
  4464.4 2129.07  4756.7 2127.38  4807.3 2124.18  4836.5 2123.95  4847.8 2125.01
  5002.7 2123.47  5007.6 2121.77  5012.4 2118.54  5012.9 2118.04  5033.0 2118.54
  5045.1 2125.02  5066.7 2127.53  5072.5 2124.55  5088.4 2127.10  5094.1 2126.14
  5110.0 2126.70  5115.8 2123.89  5125.9 2126.84  5160.6 2129.08  5412.4 2130.33
  5449.5 2130.60  5535.7 2130.76  5850.1 2135.13  6203.8 2141.85  6384.7 2147.90
#Mann=5,-1,0
  3467.1    0.07       0  5012.4    0.07       0  5033.0    0.07       0
  5412.4   0.035       0  5449.5    0.07       0
Bank Sta=5012.4,5033
Exp/Cntr=0.3,0.1

Type RM Length L Ch R = 1,58500,500,500,500
BEGIN DESCRIPTION:
Sweetwater Creek Trib 27 116.0
END DESCRIPTION:
XS GIS Cut Line= 3
      1369272.28      6879732.78      1369257.93      6878684.18
      1369355.00      6876688.03
#Sta/Elev= 30
  3951.3 2138.19  4146.1 2130.21  4426.1 2125.47  4606.1 2127.59  4636.1 2126.73
  4706.1 2127.50  4816.2 2125.41  4896.2 2125.11  4906.2 2126.38  4936.2 2124.79
  4966.2 2121.60  5000.0 2121.08  5005.9 2114.81  5006.4 2114.31  5026.5 2114.81
  5036.2 2122.59  5056.2 2125.93  5078.2 2126.49  5166.4 2128.11  5292.2 2126.13
  5710.0 2127.95  5755.0 2128.63  5899.4 2129.29  5960.2 2130.46  6057.4 2132.28
  6217.6 2138.45  6467.9 2145.67  6808.8 2163.08  6822.4 2163.60  6998.5 2170.16
#Mann=11,-1,0
  3951.3    0.07       0  5005.9    0.07       0  5026.5    0.07       0
  5078.2   0.035       0  5292.2    0.07       0  5710.0    0.16       0
  5755.0    0.07       0  5899.4    0.16       0  5960.2    0.07       0
  6808.8   0.035       0  6822.4    0.07       0
Bank Sta=5005.9,5026.5
Exp/Cntr=0.3,0.1

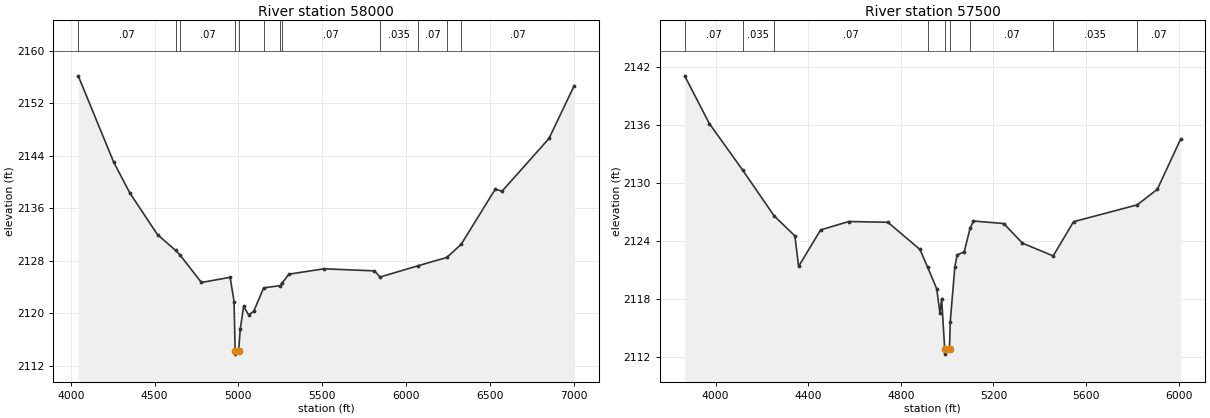
Type RM Length L Ch R = 1,58000,500,500,500
BEGIN DESCRIPTION:
Sweetwater Creek Trib 27 115.0
END DESCRIPTION:
XS GIS Cut Line= 3
      1369405.00      6879988.02      1369513.14      6879038.96
      1369455.00      6877038.00
#Sta/Elev= 30
  4044.8 2156.22  4256.2 2143.06  4352.9 2138.33  4517.9 2131.98  4625.8 2129.58
  4649.5 2128.96  4779.5 2124.69  4950.6 2125.48  4974.0 2121.78  4980.6 2114.26
  4981.1 2113.76  5001.2 2114.26  5011.0 2117.58  5031.0 2121.03  5061.0 2119.75
  5091.0 2120.28  5150.6 2123.87  5248.6 2124.21  5261.4 2124.63  5301.1 2125.96
  5511.2 2126.78  5811.3 2126.46  5844.3 2125.52  6072.0 2127.25  6242.6 2128.51
  6328.1 2130.51  6531.6 2138.94  6571.6 2138.61  6851.7 2146.66  7001.8 2154.70
#Mann=12,-1,0
  4044.8    0.07       0  4625.8   0.035       0  4649.5    0.07       0
  4980.6    0.07       0  5001.2    0.07       0  5150.6    0.07       0
  5248.6    0.16       0  5261.4    0.07       0  5844.3   0.035       0
  6072.0    0.07       0  6242.6   0.035       0  6328.1    0.07       0
Bank Sta=4980.6,5001.2
Exp/Cntr=0.3,0.1

Type RM Length L Ch R = 1,57500,500,500,500
BEGIN DESCRIPTION:
Sweetwater Creek Trib 27 114.0
END DESCRIPTION:
XS GIS Cut Line= 4
      1369583.50      6879728.21      1369741.17      6878724.18
      1369658.23      6878641.27      1369555.00      6877637.97
#Sta/Elev= 30
  3866.4 2141.04  3972.8 2136.11  4116.2 2131.32  4252.6 2126.57  4342.4 2124.49
  4358.5 2121.34  4453.7 2125.11  4575.2 2125.98  4744.2 2125.90  4882.7 2123.09
  4915.8 2121.26  4955.1 2119.02  4969.2 2116.48  4976.3 2118.02  4989.7 2112.77
  4990.2 2112.27  5010.3 2112.77  5013.3 2115.55  5033.4 2121.31  5043.5 2122.53
  5073.7 2122.84  5099.1 2125.27  5113.9 2126.03  5244.6 2125.77  5325.0 2123.75
  5458.0 2122.42  5546.1 2125.96  5821.0 2127.70  5908.0 2129.31  6008.6 2134.49
#Mann=9,-1,0
  3866.4    0.07       0  4116.2   0.035       0  4252.6    0.07       0
  4915.8    0.16       0  4989.7    0.07       0  5010.3    0.16       0
  5099.1    0.07       0  5458.0   0.035       0  5821.0    0.07       0
Bank Sta=4989.7,5010.3
Exp/Cntr=0.3,0.1