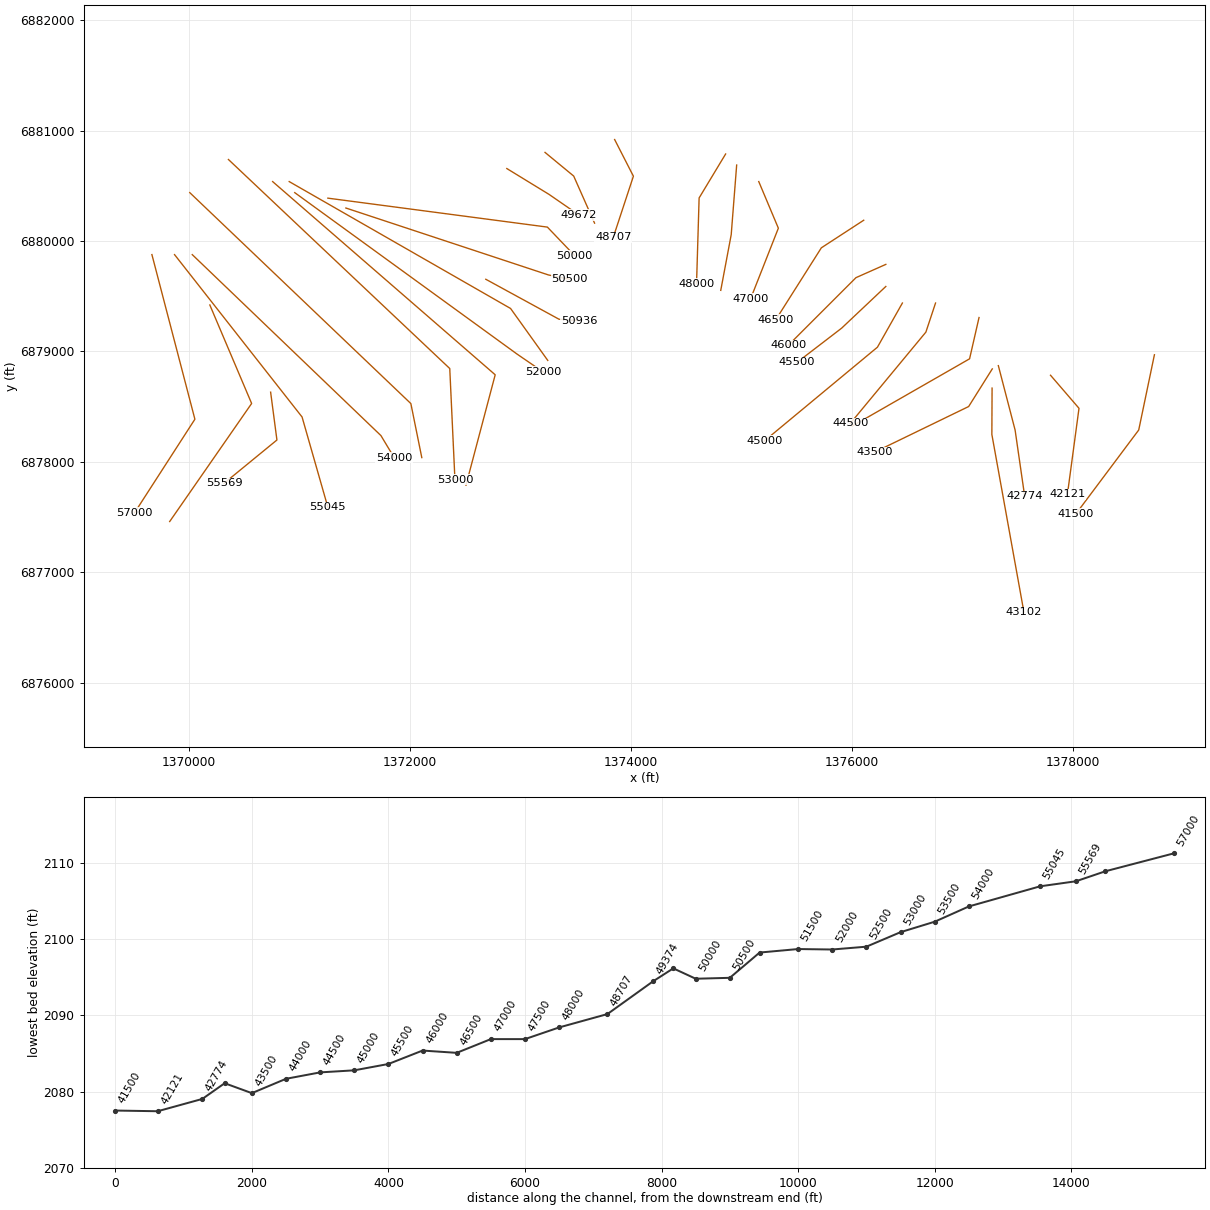
HEC-RAS study Sweetwater Creek Trib 27.prj: Sweetwater Creek Trib 27 Base Level Engineering

--- Sweetwater Creek Trib 27.g01 (geometry) --- (continued)

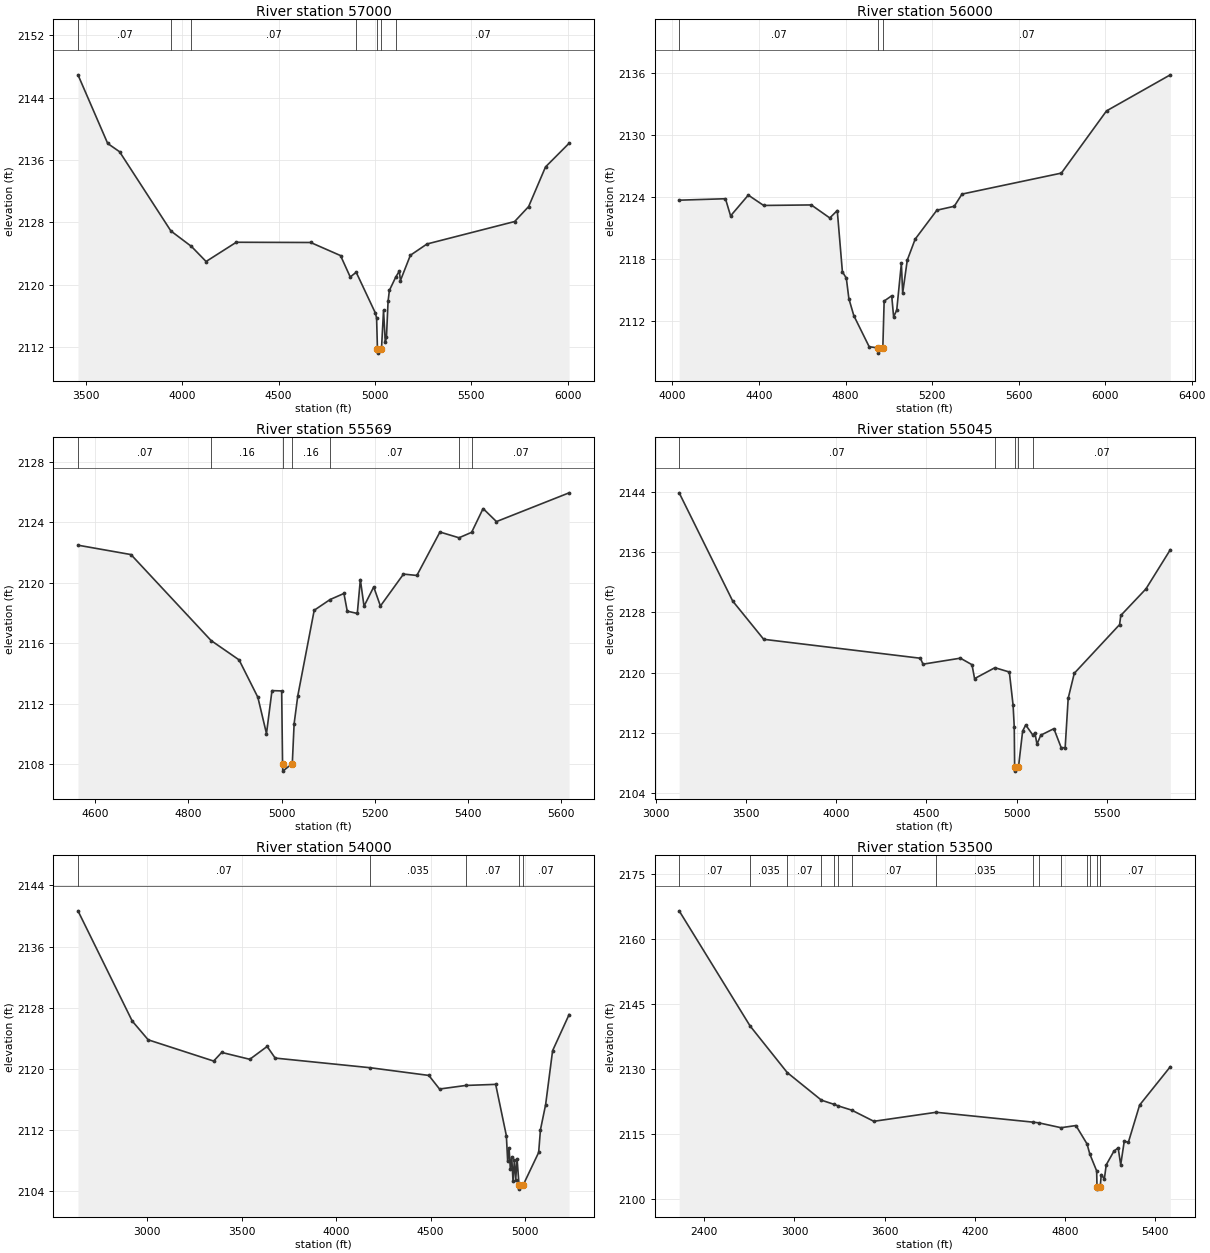
Type RM Length L Ch R = 1,57000,1000,1000,1000
BEGIN DESCRIPTION:
Sweetwater Creek Trib 27 113.0
END DESCRIPTION:
XS GIS Cut Line= 3
      1369662.24      6879876.88      1370051.28      6878385.49
      1369505.00      6877538.00
#Sta/Elev= 30
  3458.7 2146.92  3613.0 2138.11  3674.6 2137.05  3941.0 2126.88  4047.9 2124.89
  4123.7 2122.96  4280.5 2125.43  4666.7 2125.40  4821.7 2123.72  4872.1 2120.97
  4903.0 2121.58  5002.7 2116.34  5008.9 2115.69  5013.4 2111.70  5013.9 2111.20
  5034.2 2111.70  5044.9 2116.69  5054.1 2112.61  5060.1 2113.24  5068.4 2117.83
  5075.3 2119.25  5108.1 2120.95  5126.8 2121.73  5132.7 2120.52  5184.2 2123.76
  5270.7 2125.21  5725.5 2128.09  5798.1 2130.01  5885.8 2135.10  6008.3 2138.14
#Mann=7,-1,0
  3458.7    0.07       0  3941.0   0.035       0  4047.9    0.07       0
  4903.0    0.16       0  5013.4    0.07       0  5034.2    0.16       0
  5108.1    0.07       0
Bank Sta=5013.4,5034.2
Exp/Cntr=0.3,0.1

Type RM Length L Ch R = 1,56000,431,431,431
BEGIN DESCRIPTION:
Sweetwater Creek Trib 27 112.0
END DESCRIPTION:
XS GIS Cut Line= 3
      1370186.56      6879420.26      1370564.87      6878528.16
      1369823.21      6877458.90
#Sta/Elev= 30
  4031.0 2123.66  4245.0 2123.80  4268.7 2122.14  4350.5 2124.15  4421.5 2123.15
  4641.7 2123.20  4727.3 2121.94  4761.8 2122.66  4785.5 2116.74  4803.7 2116.11
  4815.5 2114.13  4838.3 2112.49  4909.3 2109.48  4951.6 2109.36  4952.1 2108.86
  4972.4 2109.36  4978.5 2113.90  5013.5 2114.41  5022.3 2112.37  5036.7 2113.02
  5058.1 2117.54  5064.2 2114.67  5085.4 2117.86  5121.9 2119.89  5222.2 2122.69
  5302.6 2123.07  5338.4 2124.25  5797.7 2126.28  6006.4 2132.30  6301.3 2135.79
#Mann=3,-1,0
  4031.0    0.07       0  4951.6    0.07       0  4972.4    0.07       0
Bank Sta=4951.6,4972.4
Exp/Cntr=0.3,0.1

Type RM Length L Ch R = 1,55569,524,524,524
BEGIN DESCRIPTION:
Sweetwater Creek Trib 27 111.0
END DESCRIPTION:
XS GIS Cut Line= 3
      1370736.83      6878630.70      1370793.81      6878197.33
      1370316.68      6877806.45
#Sta/Elev= 30
  4562.9 2122.48  4676.6 2121.86  4848.5 2116.18  4908.6 2114.90  4948.9 2112.43
  4967.4 2110.03  4979.2 2112.87  5000.0 2112.85  5001.9 2108.05  5002.4 2107.55
  5022.8 2108.05  5026.7 2110.68  5034.6 2112.53  5069.8 2118.18  5104.0 2118.89
  5133.6 2119.29  5140.7 2118.12  5162.3 2117.97  5168.8 2120.21  5176.7 2118.45
  5197.5 2119.72  5211.9 2118.46  5261.4 2120.57  5290.1 2120.48  5339.6 2123.35
  5380.5 2122.97  5407.6 2123.33  5432.2 2124.90  5460.9 2124.04  5616.8 2125.94
#Mann=7,-1,0
  4562.9    0.07       0  4848.5    0.16       0  5001.9    0.07       0
  5022.8    0.16       0  5104.0    0.07       0  5380.5    0.16       0
  5407.6    0.07       0
Bank Sta=5001.9,5022.8
Exp/Cntr=0.3,0.1

Type RM Length L Ch R = 1,55045,1045,1045,1045
BEGIN DESCRIPTION:
Sweetwater Creek Trib 27 110.0
END DESCRIPTION:
XS GIS Cut Line= 3
      1369867.13      6879876.53      1371021.43      6878405.69
      1371255.00      6877588.00
#Sta/Elev= 30
  3130.3 2143.92  3426.8 2129.52  3598.5 2124.43  4466.3 2121.91  4480.8 2121.12
  4687.8 2121.92  4752.0 2121.05  4766.4 2119.20  4878.8 2120.65  4958.9 2120.08
  4979.7 2115.66  4986.1 2112.75  4988.3 2107.39  4988.8 2106.89  5009.3 2107.39
  5032.6 2112.23  5049.6 2113.03  5090.2 2111.65  5100.2 2112.01  5112.0 2110.47
  5132.8 2111.67  5205.6 2112.54  5245.8 2110.03  5268.0 2109.99  5284.8 2116.58
  5318.6 2119.91  5569.6 2126.39  5576.1 2127.60  5715.2 2131.13  5850.4 2136.35
#Mann=5,-1,0
  3130.3    0.07       0  4878.8    0.16       0  4988.3    0.07       0
  5009.3    0.16       0  5090.2    0.07       0
Bank Sta=4988.3,5009.3
Exp/Cntr=0.3,0.1

Type RM Length L Ch R = 1,54000,500,500,500
BEGIN DESCRIPTION:
Sweetwater Creek Trib 27 108.0
END DESCRIPTION:
XS GIS Cut Line= 3
      1370027.70      6879876.23      1371735.07      6878237.43
      1371854.99      6878038.01
#Sta/Elev= 30
  2633.4 2140.67  2920.4 2126.25  3005.0 2123.79  3351.5 2121.01  3394.0 2122.14
  3542.7 2121.24  3634.5 2122.92  3677.0 2121.40  4179.0 2120.14  4490.2 2119.13
  4546.9 2117.35  4686.7 2117.82  4844.0 2117.96  4900.6 2111.24  4907.6 2107.87
  4914.8 2109.66  4921.7 2106.86  4928.9 2108.45  4935.9 2105.27  4943.1 2108.08
  4950.0 2105.49  4957.2 2108.23  4967.8 2104.75  4968.3 2104.25  4988.8 2104.75
  5071.5 2109.05  5081.0 2112.02  5108.4 2115.31  5145.3 2122.37  5232.7 2127.10
#Mann=5,-1,0
  2633.4    0.07       0  4179.0   0.035       0  4686.7    0.07       0
  4967.8    0.07       0  4988.8    0.07       0
Bank Sta=4967.8,4988.8
Exp/Cntr=0.3,0.1

Type RM Length L Ch R = 1,53500,500,500,500
BEGIN DESCRIPTION:
Sweetwater Creek Trib 27 107.0
END DESCRIPTION:
XS GIS Cut Line= 3
      1370005.01      6880437.99      1372006.03      6878527.36
      1372105.01      6878037.97
#Sta/Elev= 30
  2233.3 2166.50  2704.7 2139.93  2951.9 2129.16  3179.1 2122.79  3263.3 2121.82
  3292.2 2121.45  3380.4 2120.49  3527.7 2117.91  3942.2 2119.99  4584.5 2117.72
  4624.6 2117.55  4772.7 2116.43  4871.6 2116.93  4945.5 2112.69  4963.9 2110.36
  5009.5 2106.46  5011.9 2102.75  5012.4 2102.25  5032.9 2102.75  5034.1 2103.22
  5040.2 2105.62  5060.6 2104.58  5073.2 2107.86  5123.9 2110.99  5152.4 2111.79
  5169.5 2107.87  5193.2 2113.35  5220.3 2113.05  5295.2 2121.66  5499.3 2130.51
#Mann=16,-1,0
  2233.3    0.07       0  2704.7   0.035       0  2951.9    0.07       0
  3179.1   0.035       0  3263.3    0.07       0  3292.2   0.035       0
  3380.4    0.07       0  3942.2   0.035       0  4584.5    0.07       0
  4624.6   0.035       0  4772.7    0.07       0  4945.5   0.035       0
  4963.9    0.16       0  5011.9    0.07       0  5032.9    0.16       0
  5034.1    0.07       0
Bank Sta=5011.9,5032.9
Exp/Cntr=0.3,0.1

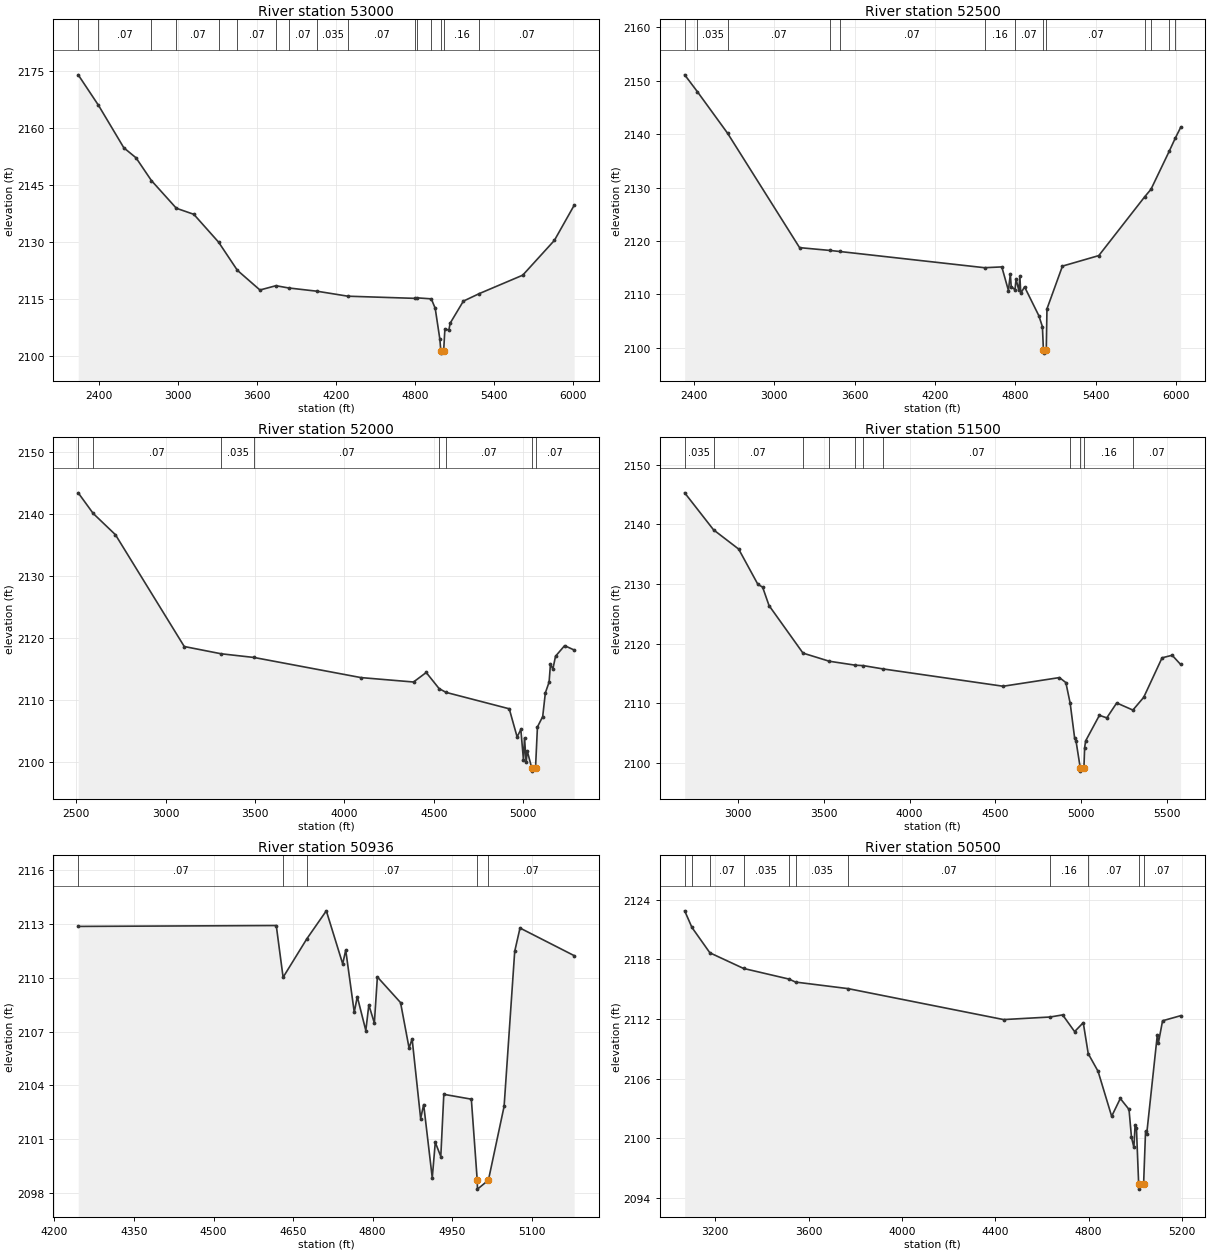
Type RM Length L Ch R = 1,53000,500,500,500
BEGIN DESCRIPTION:
Sweetwater Creek Trib 27 106.0
END DESCRIPTION:
XS GIS Cut Line= 3
      1370354.99      6880738.01      1372358.15      6878844.73
      1372405.00      6877838.02
#Sta/Elev= 30
  2243.7 2174.11  2397.5 2166.09  2590.2 2154.90  2682.4 2152.28  2799.5 2146.28
  2988.6 2139.00  3121.0 2137.41  3309.2 2130.08  3451.5 2122.68  3623.0 2117.49
  3744.5 2118.62  3840.3 2118.03  4056.1 2117.17  4290.4 2115.86  4798.8 2115.29
  4813.5 2115.43  4923.5 2115.16  4953.2 2112.68  4988.4 2104.58  4996.2 2101.38
  4996.7 2100.88  5017.2 2101.38  5026.8 2107.27  5056.8 2106.93  5066.8 2108.76
  5166.9 2114.56  5288.2 2116.55  5617.4 2121.39  5857.7 2130.54  6007.8 2139.77
#Mann=16,-1,0
  2243.7    0.16       0  2397.5    0.07       0  2799.5   0.035       0
  2988.6    0.07       0  3309.2   0.035       0  3451.5    0.07       0
  3744.5   0.035       0  3840.3    0.07       0  4056.1   0.035       0
  4290.4    0.07       0  4798.8    0.16       0  4813.5    0.07       0
  4923.5    0.16       0  4996.2    0.07       0  5017.2    0.16       0
  5288.2    0.07       0
Bank Sta=4996.2,5017.2
Exp/Cntr=0.3,0.1

Type RM Length L Ch R = 1,52500,500,500,500
BEGIN DESCRIPTION:
Sweetwater Creek Trib 27 105.0
END DESCRIPTION:
XS GIS Cut Line= 3
      1370755.02      6880537.98      1372769.43      6878788.13
      1372505.00      6877787.99
#Sta/Elev= 30
  2331.7 2151.11  2426.0 2147.97  2652.0 2140.17  3189.6 2118.74  3413.7 2118.22
  3488.1 2118.02  4570.3 2114.98  4699.5 2115.13  4748.8 2110.71  4763.1 2113.81
  4769.7 2111.44  4797.9 2110.85  4805.8 2112.83  4826.7 2110.74  4834.3 2113.40
  4840.9 2110.18  4869.4 2111.39  4975.8 2106.00  5002.7 2103.93  5010.3 2099.48
  5010.8 2098.98  5031.4 2099.48  5036.6 2107.27  5152.2 2115.28  5423.6 2117.25
  5766.4 2128.27  5813.2 2129.67  5950.4 2136.85  5993.5 2139.19  6034.5 2141.25
#Mann=13,-1,0
  2331.7    0.07       0  2426.0   0.035       0  2652.0    0.07       0
  3413.7   0.035       0  3488.1    0.07       0  4570.3    0.16       0
  4797.9    0.07       0  5010.3    0.07       0  5031.4    0.07       0
  5766.4   0.035       0  5813.2    0.07       0  5950.4   0.035       0
  5993.5    0.07       0
Bank Sta=5010.3,5031.4
Exp/Cntr=0.3,0.1

Type RM Length L Ch R = 1,52000,500,500,500
BEGIN DESCRIPTION:
Sweetwater Creek Trib 27 104.0
END DESCRIPTION:
XS GIS Cut Line= 3
      1370954.97      6880438.02      1372968.84      6878974.47
      1373204.46      6878813.07
#Sta/Elev= 30
  2510.5 2143.39  2594.4 2140.07  2718.8 2136.65  3103.9 2118.66  3310.7 2117.49
  3493.6 2116.90  4092.8 2113.66  4386.7 2112.95  4457.9 2114.48  4529.9 2111.89
  4568.8 2111.28  4922.4 2108.64  4966.4 2104.12  4987.3 2105.31  5002.0 2100.41
  5008.1 2103.95  5016.9 2100.01  5023.0 2101.88  5048.3 2099.11  5048.8 2098.61
  5069.4 2099.11  5080.2 2105.72  5109.6 2107.39  5124.5 2111.21  5145.5 2112.94
  5152.9 2115.81  5166.5 2115.04  5181.4 2117.10  5232.2 2118.80  5285.6 2118.10
#Mann=8,-1,0
  2510.5   0.035       0  2594.4    0.07       0  3310.7   0.035       0
  3493.6    0.07       0  4529.9    0.16       0  4568.8    0.07       0
  5048.3    0.07       0  5069.4    0.07       0
Bank Sta=5048.3,5069.4
Exp/Cntr=0.3,0.1

Type RM Length L Ch R = 1,51500,564,564,564
BEGIN DESCRIPTION:
Sweetwater Creek Trib 27 103.0
END DESCRIPTION:
XS GIS Cut Line= 3
      1370904.99      6880538.01      1372908.64      6879388.66
      1373245.18      6878918.25
#Sta/Elev= 30
  2690.1 2145.29  2858.3 2139.09  3004.4 2135.87  3116.6 2129.95  3143.9 2129.50
  3181.3 2126.41  3379.2 2118.44  3532.0 2117.08  3683.3 2116.42  3731.4 2116.34
  3845.3 2115.79  4544.8 2112.89  4872.7 2114.34  4910.1 2113.50  4935.3 2110.02
  4961.2 2104.20  4969.1 2103.75  4994.1 2099.17  4994.6 2098.67  5015.2 2099.17
  5019.4 2102.62  5025.5 2103.75  5105.4 2108.02  5148.4 2107.59  5206.1 2110.09
  5300.4 2108.90  5363.4 2111.03  5470.3 2117.65  5529.2 2118.08  5578.4 2116.54
#Mann=11,-1,0
  2690.1   0.035       0  2858.3    0.07       0  3379.2   0.035       0
  3532.0   0.035       0  3683.3    0.07       0  3731.4   0.035       0
  3845.3    0.07       0  4935.3    0.16       0  4994.1    0.07       0
  5015.2    0.16       0  5300.4    0.07       0
Bank Sta=4994.1,5015.2
Exp/Cntr=0.3,0.1

Type RM Length L Ch R = 1,50936,436,436,436
BEGIN DESCRIPTION:
Sweetwater Creek Trib 27 102.0
END DESCRIPTION:
XS GIS Cut Line= 3
      1372684.37      6879653.25      1373347.13      6879291.20
      1373526.84      6879279.33
#Sta/Elev= 30
  4244.8 2112.87  4618.3 2112.92  4631.2 2110.03  4676.0 2112.18  4712.7 2113.74
  4743.6 2110.78  4749.3 2111.55  4765.4 2108.08  4771.1 2108.95  4787.2 2107.06
  4792.9 2108.49  4803.3 2107.48  4809.0 2110.05  4852.7 2108.62  4868.8 2106.08
  4874.5 2106.60  4890.6 2102.15  4896.3 2102.93  4912.5 2098.84  4918.2 2100.82
  4928.6 2100.03  4934.3 2103.50  4986.2 2103.23  4997.3 2098.71  4997.8 2098.21
  5018.4 2098.71  5048.0 2102.83  5068.0 2111.48  5078.0 2112.78  5180.1 2111.24
#Mann=5,-1,0
  4244.8    0.07       0  4631.2    0.16       0  4676.0    0.07       0
  4997.3    0.07       0  5018.4    0.07       0
Bank Sta=4997.3,5018.4
Exp/Cntr=0.3,0.1

Type RM Length L Ch R = 1,50500,500,500,500
BEGIN DESCRIPTION:
Sweetwater Creek Trib 27 101.0
END DESCRIPTION:
XS GIS Cut Line= 3
      1371417.80      6880298.66      1373250.70      6879692.61
      1373440.68      6879653.32
#Sta/Elev= 30
  3069.5 2122.87  3100.6 2121.20  3177.5 2118.65  3321.6 2117.08  3516.5 2116.01
  3544.3 2115.71  3769.9 2115.05  4435.8 2111.94  4635.4 2112.20  4688.6 2112.41
  4739.9 2110.73  4776.9 2111.63  4798.3 2108.51  4840.4 2106.74  4898.6 2102.22
  4935.6 2104.01  4972.9 2102.91  4983.5 2100.11  4993.8 2099.10  4999.0 2101.33
  5004.7 2101.05  5014.3 2095.40  5014.8 2094.90  5035.4 2095.40  5043.8 2100.73
  5048.9 2100.49  5094.0 2110.36  5099.1 2109.63  5116.7 2111.82  5194.0 2112.33
#Mann=11,-1,0
  3069.5    0.07       0  3100.6   0.035       0  3177.5    0.07       0
  3321.6   0.035       0  3516.5    0.07       0  3544.3   0.035       0
  3769.9    0.07       0  4635.4    0.16       0  4798.3    0.07       0
  5014.3    0.07       0  5035.4    0.07       0
Bank Sta=5014.3,5035.4
Exp/Cntr=0.3,0.1

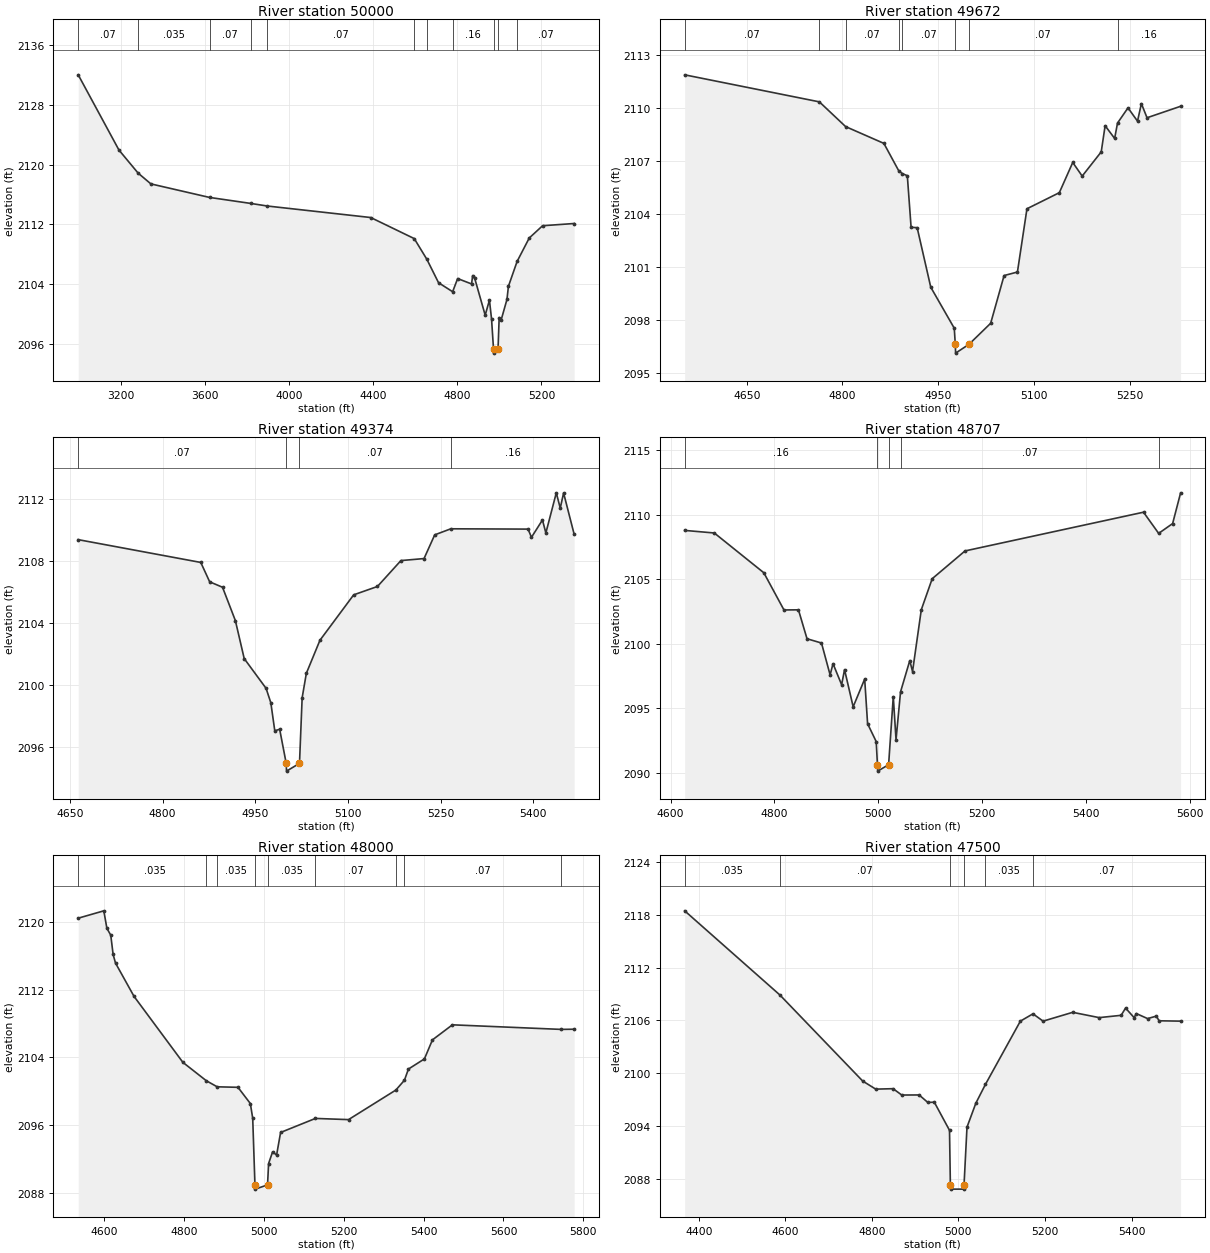
Type RM Length L Ch R = 1,50000,328,328,328
BEGIN DESCRIPTION:
Sweetwater Creek Trib 27 100.0
END DESCRIPTION:
XS GIS Cut Line= 3
      1371255.03      6880388.00      1373241.81      6880125.80
      1373487.71      6879868.52
#Sta/Elev= 30
  2996.0 2132.03  3189.9 2121.96  3281.2 2118.87  3341.9 2117.43  3620.8 2115.62
  3816.3 2114.82  3896.0 2114.47  4387.9 2112.93  4595.0 2110.11  4655.0 2107.34
  4710.7 2104.20  4777.7 2103.00  4801.5 2104.76  4867.8 2104.04  4872.9 2105.16
  4882.2 2104.84  4932.6 2099.86  4952.8 2101.87  4962.9 2099.33  4972.3 2095.28
  4972.8 2094.78  4993.7 2095.28  4999.1 2099.54  5007.9 2099.15  5036.2 2101.97
  5043.1 2103.72  5084.4 2107.05  5142.2 2110.19  5205.7 2111.83  5355.9 2112.13
#Mann=11,-1,0
  2996.0    0.07       0  3281.2   0.035       0  3620.8    0.07       0
  3816.3   0.035       0  3896.0    0.07       0  4595.0    0.16       0
  4655.0    0.07       0  4777.7    0.16       0  4972.3    0.07       0
  4993.7    0.16       0  5084.4    0.07       0
Bank Sta=4972.3,4993.7
Exp/Cntr=0.3,0.1

Type RM Length L Ch R = 1,49672,298,298,298
BEGIN DESCRIPTION:
Sweetwater Creek Trib 27 99.0
END DESCRIPTION:
XS GIS Cut Line= 3
      1372874.58      6880656.26      1373255.81      6880422.66
      1373526.95      6880235.62
#Sta/Elev= 30
  4552.9 2111.89  4763.8 2110.36  4804.9 2108.96  4864.8 2108.01  4887.9 2106.47
  4893.7 2106.30  4901.5 2106.18  4907.4 2103.26  4916.9 2103.24  4938.2 2099.87
  4975.0 2097.55  4976.6 2096.64  4977.1 2096.14  4998.1 2096.64  5032.0 2097.83
  5053.0 2100.53  5073.9 2100.73  5088.8 2104.31  5139.5 2105.22  5160.5 2106.93
  5175.3 2106.16  5205.1 2107.53  5211.2 2109.01  5226.1 2108.29  5230.6 2109.16
  5247.0 2110.02  5261.9 2109.27  5268.0 2110.26  5276.8 2109.46  5329.4 2110.11
#Mann=8,-1,0
  4552.9    0.07       0  4763.8    0.16       0  4804.9    0.07       0
  4887.9    0.16       0  4893.7    0.07       0  4976.6    0.07       0
  4998.1    0.07       0  5230.6    0.16       0
Bank Sta=4976.6,4998.1
Exp/Cntr=0.3,0.1

Type RM Length L Ch R = 1,49374,667,667,667
BEGIN DESCRIPTION:
Sweetwater Creek Trib 27 98.0
END DESCRIPTION:
XS GIS Cut Line= 3
      1373220.54      6880802.27      1373480.00      6880588.00
      1373668.76      6880161.62
#Sta/Elev= 30
  4663.5 2109.36  4861.9 2107.89  4876.3 2106.64  4897.1 2106.29  4917.9 2104.14
  4932.2 2101.69  4967.6 2099.77  4975.3 2098.84  4981.7 2097.03  4989.6 2097.13
  5000.2 2094.93  5000.7 2094.43  5021.7 2094.93  5026.0 2099.16  5032.8 2100.74
  5054.8 2102.87  5109.4 2105.80  5147.9 2106.34  5185.9 2108.01  5223.3 2108.14
  5240.6 2109.67  5266.7 2110.06  5391.7 2110.04  5397.2 2109.51  5415.0 2110.63
  5420.5 2109.79  5437.4 2112.38  5443.8 2111.39  5449.2 2112.37  5466.3 2109.71
#Mann=4,-1,0
  4663.5    0.07       0  5000.2    0.07       0  5021.7    0.07       0
  5266.7    0.16       0
Bank Sta=5000.2,5021.7
Exp/Cntr=0.3,0.1

Type RM Length L Ch R = 1,48707,707,707,707
BEGIN DESCRIPTION:
Sweetwater Creek Trib 27 97.0
END DESCRIPTION:
XS GIS Cut Line= 3
      1373850.55      6880918.80      1374020.33      6880586.90
      1373838.20      6880033.40
#Sta/Elev= 30
  4627.2 2108.79  4684.3 2108.59  4779.7 2105.51  4818.5 2102.63  4846.4 2102.64
  4862.9 2100.40  4890.8 2100.07  4907.4 2097.60  4913.0 2098.47  4929.6 2096.84
  4935.2 2098.01  4951.8 2095.13  4974.0 2097.28  4979.6 2093.82  4996.2 2092.44
  4998.6 2090.65  4999.1 2090.15  5020.1 2090.65  5029.1 2095.92  5034.4 2092.58
  5043.1 2096.29  5060.9 2098.71  5066.2 2097.86  5083.1 2102.65  5104.1 2105.05
  5167.3 2107.20  5511.2 2110.20  5540.4 2108.56  5567.3 2109.32  5582.7 2111.70
#Mann=5,-1,0
  4627.2    0.16       0  4998.6    0.07       0  5020.1    0.16       0
  5043.1    0.07       0  5540.4    0.16       0
Bank Sta=4998.6,5020.1
Exp/Cntr=0.3,0.1

Type RM Length L Ch R = 1,48000,500,500,500
BEGIN DESCRIPTION:
Sweetwater Creek Trib 27 96.0
END DESCRIPTION:
XS GIS Cut Line= 3
      1374854.99      6880787.98      1374615.14      6880389.96
      1374591.81      6879613.31
#Sta/Elev= 30
  4535.3 2120.44  4599.4 2121.31  4607.1 2119.24  4616.8 2118.43  4622.7 2116.15
  4628.7 2115.13  4675.1 2111.19  4797.4 2103.39  4856.0 2101.22  4883.2 2100.50
  4935.3 2100.44  4966.3 2098.52  4972.2 2096.78  4977.8 2088.90  4978.3 2088.40
  5009.3 2088.90  5012.0 2091.43  5022.0 2092.81  5032.0 2092.43  5042.0 2095.10
  5129.2 2096.76  5212.1 2096.62  5330.7 2100.12  5352.1 2101.28  5362.1 2102.60
  5402.1 2103.80  5422.2 2106.05  5472.2 2107.83  5743.8 2107.29  5777.0 2107.31
#Mann=10,-1,0
  4535.3    0.07       0  4599.4   0.035       0  4856.0    0.07       0
  4883.2   0.035       0  4977.8   0.035       0  5009.3   0.035       0
  5129.2    0.07       0  5330.7   0.035       0  5352.1    0.07       0
  5743.8    0.16       0
Bank Sta=4977.8,5009.3
Exp/Cntr=0.3,0.1

Type RM Length L Ch R = 1,47500,500,500,500
BEGIN DESCRIPTION:
Sweetwater Creek Trib 27 95.0
END DESCRIPTION:
XS GIS Cut Line= 3
      1374955.00      6880687.97      1374905.64      6880057.50
      1374811.02      6879553.00
#Sta/Elev= 30
  4367.6 2118.43  4587.7 2108.88  4778.8 2099.13  4808.9 2098.21  4849.0 2098.26
  4869.1 2097.54  4909.2 2097.55  4929.3 2096.70  4944.3 2096.73  4979.4 2093.54
  4981.4 2087.37  4981.9 2086.87  5012.5 2086.87  5013.0 2087.37  5019.8 2093.90
  5040.2 2096.61  5062.3 2098.74  5143.1 2105.92  5172.2 2106.75  5195.6 2105.92
  5264.0 2106.92  5325.1 2106.32  5375.9 2106.58  5386.1 2107.40  5405.9 2106.32
  5411.0 2106.78  5437.0 2106.21  5457.3 2106.49  5463.5 2105.96  5513.3 2105.92
#Mann=6,-1,0
  4367.6   0.035       0  4587.7    0.07       0  4981.4    0.07       0
  5013.0    0.07       0  5062.3   0.035       0  5172.2    0.07       0
Bank Sta=4981.4,5013
Exp/Cntr=0.3,0.1

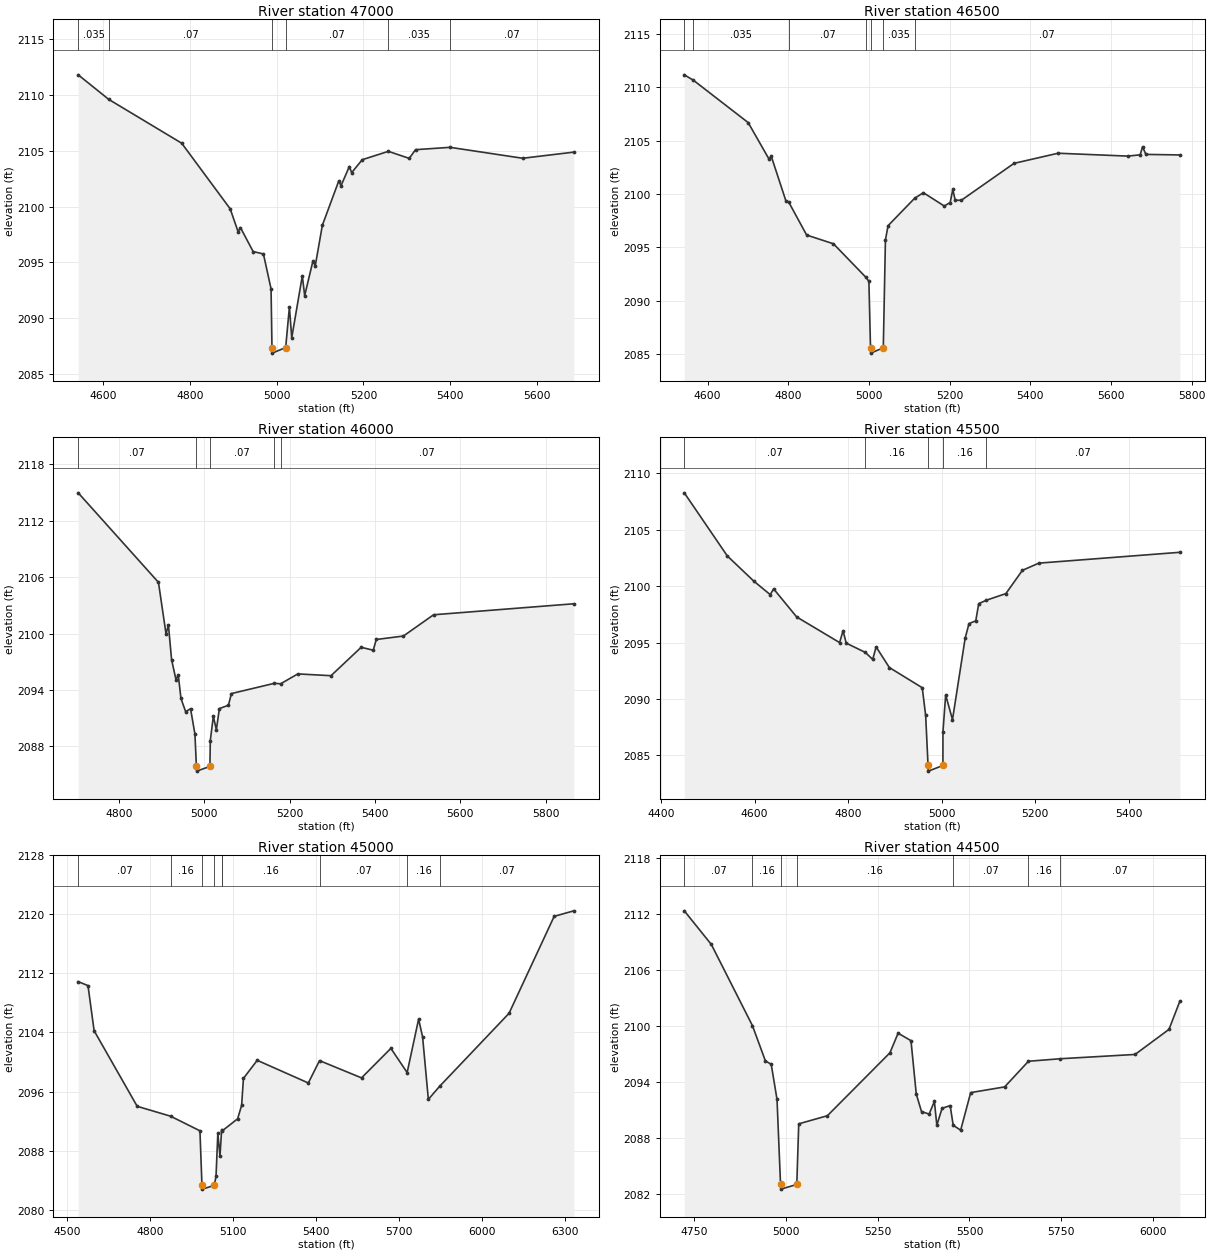
Type RM Length L Ch R = 1,47000,500,500,500
BEGIN DESCRIPTION:
Sweetwater Creek Trib 27 94.0
END DESCRIPTION:
XS GIS Cut Line= 3
      1375154.98      6880538.04      1375332.39      6880116.01
      1375081.76      6879478.29
#Sta/Elev= 30
  4542.2 2111.82  4612.6 2109.62  4780.9 2105.69  4892.7 2099.81  4911.0 2097.75
  4916.5 2098.12  4945.6 2095.98  4969.4 2095.76  4987.0 2092.63  4989.1 2087.37
  4989.6 2086.87  5020.7 2087.37  5029.3 2091.00  5034.7 2088.25  5059.1 2093.80
  5064.5 2092.02  5083.5 2095.12  5088.9 2094.69  5105.3 2098.33  5143.1 2102.30
  5148.4 2101.88  5167.5 2103.60  5172.9 2103.05  5197.3 2104.21  5257.5 2104.96
  5305.7 2104.33  5320.2 2105.11  5399.8 2105.32  5567.3 2104.34  5685.2 2104.89
#Mann=6,-1,0
  4542.2   0.035       0  4612.6    0.07       0  4989.1    0.07       0
  5020.7    0.07       0  5257.5   0.035       0  5399.8    0.07       0
Bank Sta=4989.1,5020.7
Exp/Cntr=0.3,0.1

Type RM Length L Ch R = 1,46500,500,500,500
BEGIN DESCRIPTION:
Sweetwater Creek Trib 27 93.0
END DESCRIPTION:
XS GIS Cut Line= 3
      1376104.98      6880187.99      1375721.57      6879938.20
      1375309.16      6879286.89
#Sta/Elev= 30
  4542.4 2111.16  4565.1 2110.65  4700.8 2106.68  4752.1 2103.28  4758.1 2103.51
  4794.3 2099.34  4801.1 2099.24  4845.7 2096.14  4912.2 2095.32  4992.8 2092.17
  5000.0 2091.80  5004.0 2085.57  5004.5 2085.07  5035.7 2085.57  5041.0 2095.69
  5047.6 2097.02  5113.4 2099.59  5135.1 2100.11  5186.8 2098.86  5201.5 2099.19
  5208.0 2100.41  5213.9 2099.41  5229.1 2099.40  5359.7 2102.86  5469.0 2103.81
  5641.9 2103.54  5672.4 2103.66  5678.3 2104.41  5686.7 2103.70  5770.9 2103.65
#Mann=7,-1,0
  4542.4    0.07       0  4565.1   0.035       0  4801.1    0.07       0
  4992.8   0.035       0  5004.0   0.035       0  5035.7   0.035       0
  5113.4    0.07       0
Bank Sta=5004,5035.7
Exp/Cntr=0.3,0.1

Type RM Length L Ch R = 1,46000,500,500,500
BEGIN DESCRIPTION:
Sweetwater Creek Trib 27 92.0
END DESCRIPTION:
XS GIS Cut Line= 3
      1376305.04      6879788.02      1376034.85      6879667.87
      1375422.65      6879055.65
#Sta/Elev= 30
  4704.3 2114.97  4892.4 2105.45  4910.2 2099.95  4915.7 2100.93  4923.2 2097.21
  4933.4 2095.11  4938.9 2095.58  4945.1 2093.11  4956.1 2091.69  4967.6 2092.01
  4977.9 2089.31  4981.3 2085.87  4981.8 2085.37  5013.0 2085.87  5013.9 2088.62
  5021.0 2091.20  5028.1 2089.77  5035.2 2092.02  5056.4 2092.38  5063.4 2093.62
  5164.1 2094.71  5178.7 2094.66  5219.0 2095.71  5296.8 2095.52  5367.5 2098.54
  5395.8 2098.23  5402.9 2099.37  5466.5 2099.74  5537.2 2102.00  5865.8 2103.17
#Mann=5,-1,0
  4704.3    0.07       0  4981.3    0.07       0  5013.0    0.07       0
  5164.1    0.16       0  5178.7    0.07       0
Bank Sta=4981.3,5013
Exp/Cntr=0.3,0.1

Type RM Length L Ch R = 1,45500,500,500,500
BEGIN DESCRIPTION:
Sweetwater Creek Trib 27 91.0
END DESCRIPTION:
XS GIS Cut Line= 3
      1376304.97      6879587.97      1375904.67      6879210.07
      1375500.32      6878899.59
#Sta/Elev= 30
  4449.5 2108.27  4541.5 2102.68  4598.1 2100.45  4633.3 2099.25  4640.6 2099.76
  4690.0 2097.27  4781.8 2095.00  4789.1 2096.05  4796.0 2094.95  4836.8 2094.13
  4852.6 2093.51  4859.9 2094.62  4888.2 2092.79  4958.6 2091.00  4965.9 2088.54
  4971.0 2084.11  4971.5 2083.61  5002.8 2084.11  5002.9 2087.10  5008.7 2090.36
  5023.3 2088.17  5050.4 2095.39  5058.6 2096.68  5073.1 2096.93  5079.4 2098.45
  5095.5 2098.75  5137.5 2099.34  5172.8 2101.40  5208.1 2102.04  5509.8 2103.00
#Mann=5,-1,0
  4449.5    0.07       0  4836.8    0.16       0  4971.0    0.07       0
  5002.8    0.16       0  5095.5    0.07       0
Bank Sta=4971,5002.8
Exp/Cntr=0.3,0.1

Type RM Length L Ch R = 1,45000,500,500,500
BEGIN DESCRIPTION:
Sweetwater Creek Trib 27 90.0
END DESCRIPTION:
XS GIS Cut Line= 3
      1376455.02      6879438.04      1376229.32      6879038.25
      1375205.02      6878188.01
#Sta/Elev= 30
  4540.9 2110.89  4576.3 2110.35  4598.4 2104.24  4754.0 2094.00  4874.6 2092.66
  4980.7 2090.68  4988.0 2083.28  4989.0 2082.78  5032.3 2083.28  5038.8 2084.52
  5045.3 2090.32  5053.1 2087.26  5059.1 2090.85  5061.3 2090.68  5116.9 2092.31
  5131.3 2094.14  5137.8 2097.78  5187.6 2100.23  5372.2 2097.16  5412.7 2100.19
  5564.4 2097.85  5670.4 2101.85  5729.2 2098.57  5770.6 2105.81  5785.0 2103.40
  5805.8 2094.94  5846.8 2096.72  6097.3 2106.60  6260.3 2119.73  6331.2 2120.48
#Mann=9,-1,0
  4540.9    0.07       0  4874.6    0.16       0  4988.0    0.07       0
  5032.3    0.16       0  5059.1    0.07       0  5061.3    0.16       0
  5412.7    0.07       0  5729.2    0.16       0  5846.8    0.07       0
Bank Sta=4988,5032.3
Exp/Cntr=0.3,0.1

Type RM Length L Ch R = 1,44500,500,500,500
BEGIN DESCRIPTION:
Sweetwater Creek Trib 27 89.0
END DESCRIPTION:
XS GIS Cut Line= 3
      1376755.00      6879438.01      1376667.71      6879174.60
      1375983.22      6878347.50
#Sta/Elev= 30
  4722.5 2112.35  4796.3 2108.74  4908.4 2100.03  4943.7 2096.25  4959.5 2095.90
  4975.3 2092.13  4984.9 2083.01  4985.9 2082.51  5029.2 2083.01  5034.5 2089.51
  5112.6 2090.38  5283.2 2097.13  5305.4 2099.23  5340.5 2098.43  5354.9 2092.71
  5369.2 2090.82  5390.0 2090.56  5404.3 2091.91  5411.0 2089.36  5425.2 2091.17
  5447.3 2091.47  5455.6 2089.36  5475.9 2088.83  5503.3 2092.86  5595.8 2093.47
  5660.7 2096.22  5747.4 2096.49  5951.4 2096.95  6043.9 2099.64  6073.6 2102.67
#Mann=7,-1,0
  4722.5    0.07       0  4908.4    0.16       0  4984.9    0.07       0
  5029.2    0.16       0  5455.6    0.07       0  5660.7    0.16       0
  5747.4    0.07       0
Bank Sta=4984.9,5029.2
Exp/Cntr=0.3,0.1

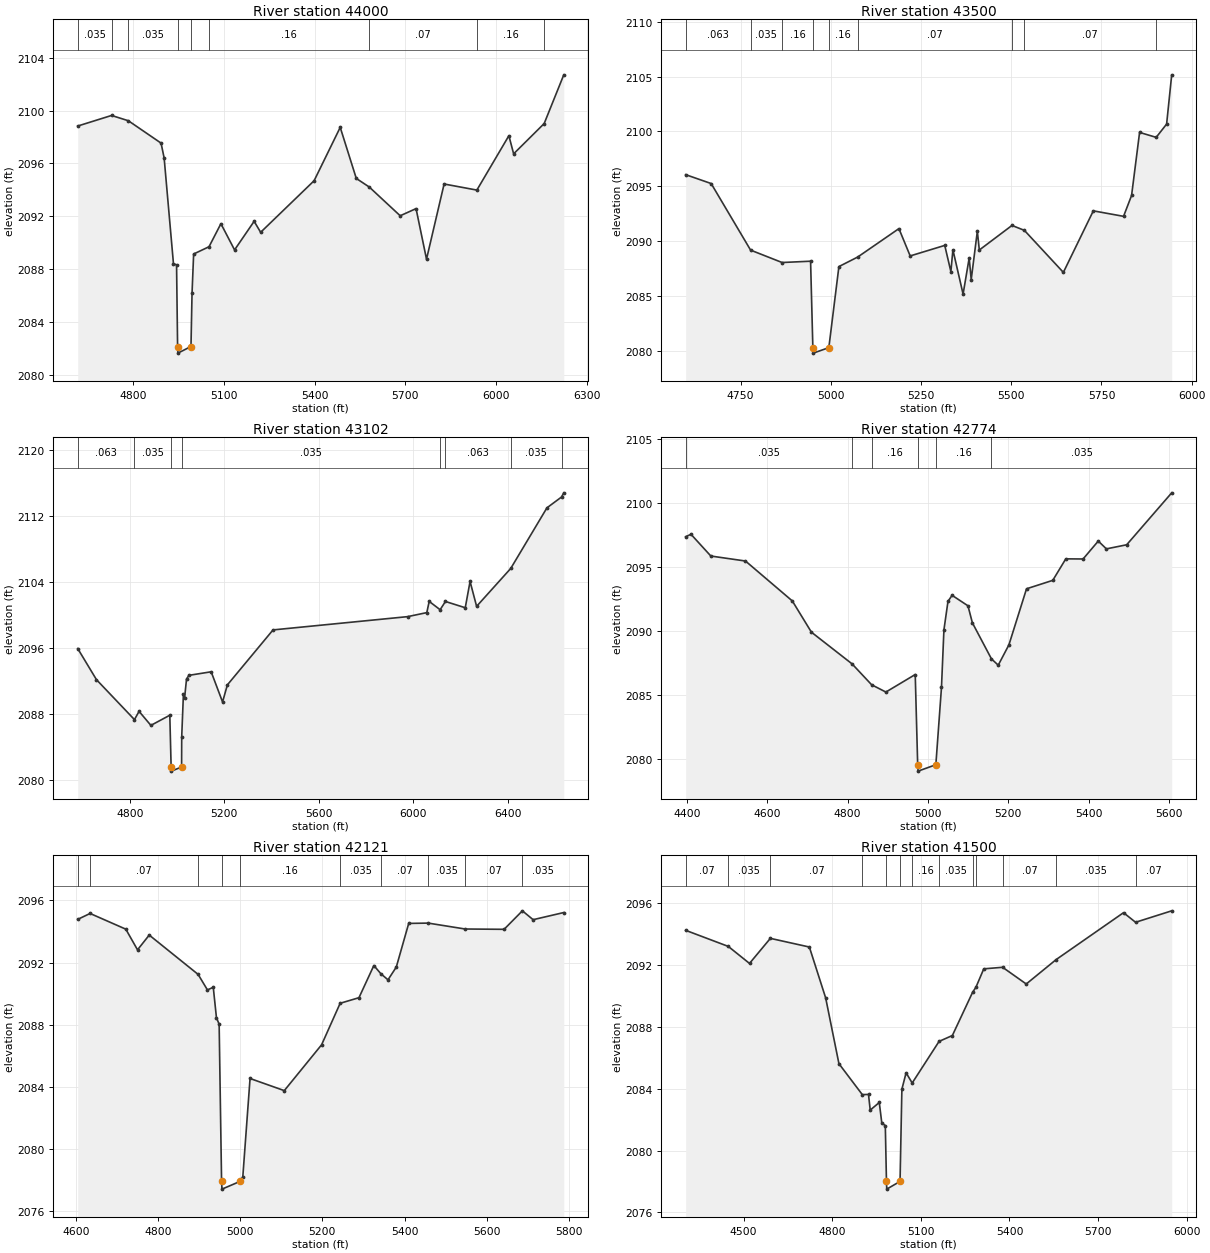
Type RM Length L Ch R = 1,44000,500,500,500
BEGIN DESCRIPTION:
Sweetwater Creek Trib 27 88.0
END DESCRIPTION:
XS GIS Cut Line= 3
      1377148.69      6879306.70      1377063.05      6878932.69
      1376001.14      6878323.37
#Sta/Elev= 30
  4616.3 2098.83  4728.3 2099.63  4783.8 2099.23  4892.0 2097.54  4902.2 2096.42
  4933.0 2088.44  4943.3 2088.34  4946.7 2082.17  4947.7 2081.67  4991.0 2082.17
  4994.5 2086.20  4999.8 2089.16  5050.7 2089.71  5090.0 2091.45  5135.2 2089.47
  5199.9 2091.63  5221.5 2090.80  5398.4 2094.70  5484.7 2098.73  5537.9 2094.87
  5580.9 2094.22  5683.1 2092.05  5735.6 2092.59  5770.2 2088.77  5828.4 2094.45
  5936.8 2093.99  6042.7 2098.10  6058.4 2096.73  6159.5 2099.02  6224.3 2102.70
#Mann=9,-1,0
  4616.3   0.035       0  4728.3   0.063       0  4783.8   0.035       0
  4946.7   0.035       0  4991.0   0.035       0  5050.7    0.16       0
  5580.9    0.07       0  5936.8    0.16       0  6159.5    0.07       0
Bank Sta=4946.7,4991
Exp/Cntr=0.3,0.1

Type RM Length L Ch R = 1,43500,398,398,398
BEGIN DESCRIPTION:
Sweetwater Creek Trib 27 87.0
END DESCRIPTION:
XS GIS Cut Line= 3
      1377268.55      6878841.30      1377054.82      6878500.59
      1376204.98      6878087.99
#Sta/Elev= 30
  4597.8 2096.06  4668.5 2095.25  4777.8 2089.18  4865.1 2088.05  4944.0 2088.17
  4950.3 2080.29  4951.3 2079.79  4994.6 2080.29  5022.5 2087.68  5074.6 2088.55
  5188.8 2091.14  5220.0 2088.65  5315.8 2089.61  5332.8 2087.22  5338.4 2089.21
  5366.6 2085.17  5383.5 2088.46  5389.1 2086.49  5406.1 2090.90  5411.6 2089.19
  5502.1 2091.43  5536.5 2090.98  5644.5 2087.15  5727.5 2092.76  5811.3 2092.26
  5833.5 2094.16  5855.7 2099.91  5901.7 2099.46  5930.6 2100.67  5944.7 2105.16
#Mann=9,-1,0
  4597.8   0.063       0  4777.8   0.035       0  4865.1    0.16       0
  4950.3    0.07       0  4994.6    0.16       0  5074.6    0.07       0
  5502.1    0.16       0  5536.5    0.07       0  5901.7    0.16       0
Bank Sta=4950.3,4994.6
Exp/Cntr=0.3,0.1

Type RM Length L Ch R = 1,43102,328,328,328
BEGIN DESCRIPTION:
Sweetwater Creek Trib 27 86.0
END DESCRIPTION:
XS GIS Cut Line= 3
      1377266.75      6878667.41      1377264.80      6878247.62
      1377555.01      6876637.97
#Sta/Elev= 30
  4580.2 2095.96  4659.6 2092.18  4820.1 2087.34  4839.6 2088.34  4889.6 2086.64
  4969.6 2087.87  4975.2 2081.59  4976.2 2081.09  5019.5 2081.59  5019.9 2085.21
  5027.2 2090.45  5032.2 2090.00  5040.3 2092.25  5050.4 2092.71  5144.5 2093.14
  5192.7 2089.48  5213.0 2091.55  5406.1 2098.22  5975.1 2099.83  6056.4 2100.32
  6066.5 2101.68  6112.7 2100.67  6135.2 2101.67  6219.0 2100.91  6239.3 2104.10
  6267.0 2101.08  6411.4 2105.68  6564.4 2113.03  6626.0 2114.34  6635.6 2114.85
#Mann=8,-1,0
  4580.2   0.063       0  4820.1   0.035       0  4975.2   0.035       0
  5019.5   0.035       0  6112.7    0.07       0  6135.2   0.063       0
  6411.4   0.035       0  6626.0    0.07       0
Bank Sta=4975.2,5019.5
Exp/Cntr=0.3,0.1

Type RM Length L Ch R = 1,42774,653,653,653
BEGIN DESCRIPTION:
Sweetwater Creek Trib 27 85.0
END DESCRIPTION:
XS GIS Cut Line= 3
      1377323.47      6878870.83      1377475.16      6878287.53
      1377561.88      6877687.17
#Sta/Elev= 30
  4397.3 2097.35  4410.6 2097.54  4460.0 2095.84  4546.2 2095.45  4662.7 2092.33
  4710.2 2089.89  4811.4 2087.41  4860.0 2085.78  4895.5 2085.21  4968.5 2086.58
  4974.6 2079.53  4975.6 2079.03  5019.8 2079.53  5033.8 2085.57  5039.9 2090.07
  5050.0 2092.30  5060.2 2092.77  5099.7 2091.95  5110.7 2090.62  5158.2 2087.80
  5175.0 2087.31  5201.6 2088.90  5245.4 2093.28  5310.7 2093.94  5343.1 2095.62
  5386.1 2095.61  5423.9 2097.01  5444.1 2096.40  5494.6 2096.72  5606.6 2100.78
#Mann=6,-1,0
  4397.3   0.035       0  4811.4    0.07       0  4860.0    0.16       0
  4974.6    0.07       0  5019.8    0.16       0  5158.2   0.035       0
Bank Sta=4974.6,5019.8
Exp/Cntr=0.3,0.1

Type RM Length L Ch R = 1,42121,621,621,621
BEGIN DESCRIPTION:
Sweetwater Creek Trib 27 84.0
END DESCRIPTION:
XS GIS Cut Line= 3
      1377795.70      6878783.98      1378053.53      6878484.47
      1377948.48      6877704.11
#Sta/Elev= 30
  4604.8 2094.78  4634.9 2095.16  4721.8 2094.15  4750.3 2092.82  4778.8 2093.77
  4897.7 2091.24  4920.4 2090.24  4934.6 2090.41  4942.3 2088.46  4948.9 2088.03
  4954.8 2077.92  4955.8 2077.42  5000.0 2077.92  5006.5 2078.22  5024.1 2084.54
  5107.4 2083.76  5198.2 2086.71  5243.3 2089.38  5289.1 2089.74  5325.3 2091.81
  5342.4 2091.28  5359.7 2090.89  5379.9 2091.71  5410.1 2094.52  5457.6 2094.54
  5547.4 2094.16  5642.2 2094.14  5686.7 2095.33  5712.8 2094.76  5787.4 2095.22
#Mann=10,-1,0
  4604.8   0.035       0  4634.9    0.07       0  4897.7    0.16       0
  4954.8    0.07       0  5000.0    0.16       0  5243.3   0.035       0
  5342.4    0.07       0  5457.6   0.035       0  5547.4    0.07       0
  5686.7   0.035       0
Bank Sta=4954.8,5000
Exp/Cntr=0.3,0.1

Type RM Length L Ch R = 1,41500,500,500,500
BEGIN DESCRIPTION:
Sweetwater Creek Trib 27 83.0
END DESCRIPTION:
XS GIS Cut Line= 3
      1378736.16      6878969.66      1378594.09      6878288.01
      1378025.51      6877528.07
#Sta/Elev= 30
  4303.7 2094.24  4448.0 2093.20  4519.9 2092.10  4590.5 2093.72  4722.5 2093.16
  4777.7 2089.87  4822.6 2085.62  4901.7 2083.62  4922.7 2083.63  4928.5 2082.62
  4959.2 2083.11  4967.6 2081.80  4979.6 2081.61  4983.5 2078.01  4984.5 2077.51
  5029.5 2078.01  5035.7 2083.97  5050.0 2085.03  5070.6 2084.37  5161.6 2087.06
  5206.6 2087.44  5275.0 2090.23  5286.4 2090.56  5312.9 2091.75  5376.7 2091.85
  5456.7 2090.77  5558.0 2092.35  5786.0 2095.38  5826.8 2094.76  5949.1 2095.50
#Mann=13,-1,0
  4303.7    0.07       0  4448.0   0.035       0  4590.5    0.07       0
  4901.7    0.16       0  4983.5    0.07       0  5029.5    0.16       0
  5070.6    0.16       0  5161.6   0.035       0  5275.0    0.07       0
  5286.4   0.035       0  5376.7    0.07       0  5558.0   0.035       0
  5826.8    0.07       0
Bank Sta=4983.5,5029.5
Exp/Cntr=0.3,0.1