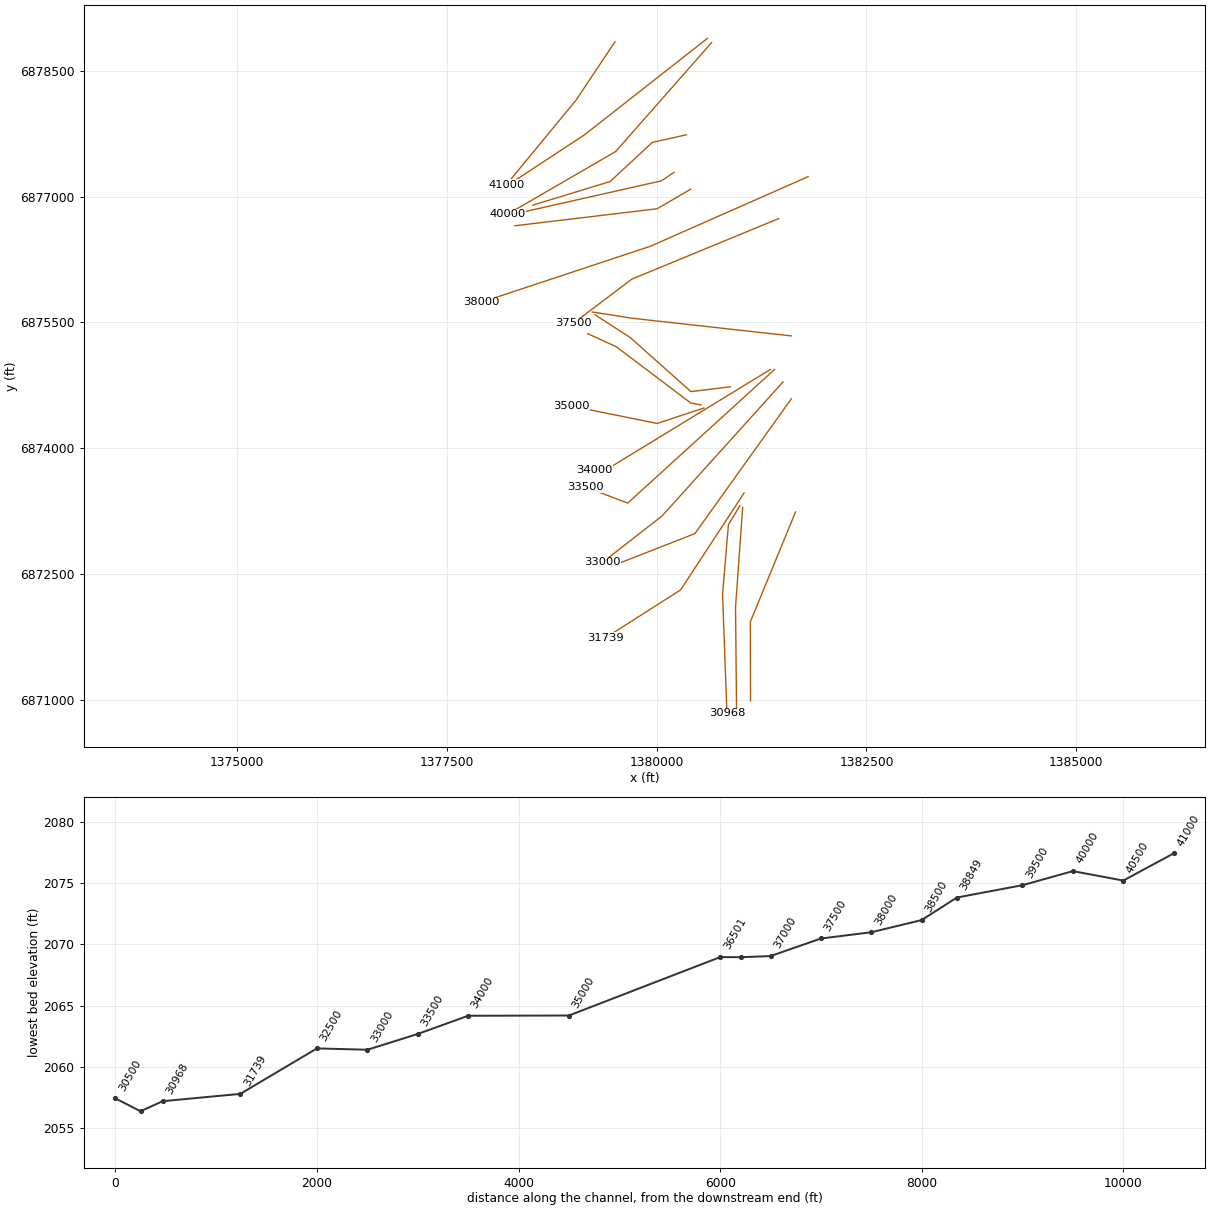
HEC-RAS study Sweetwater Creek Trib 27.prj: Sweetwater Creek Trib 27 Base Level Engineering

--- Sweetwater Creek Trib 27.g01 (geometry) --- (continued)

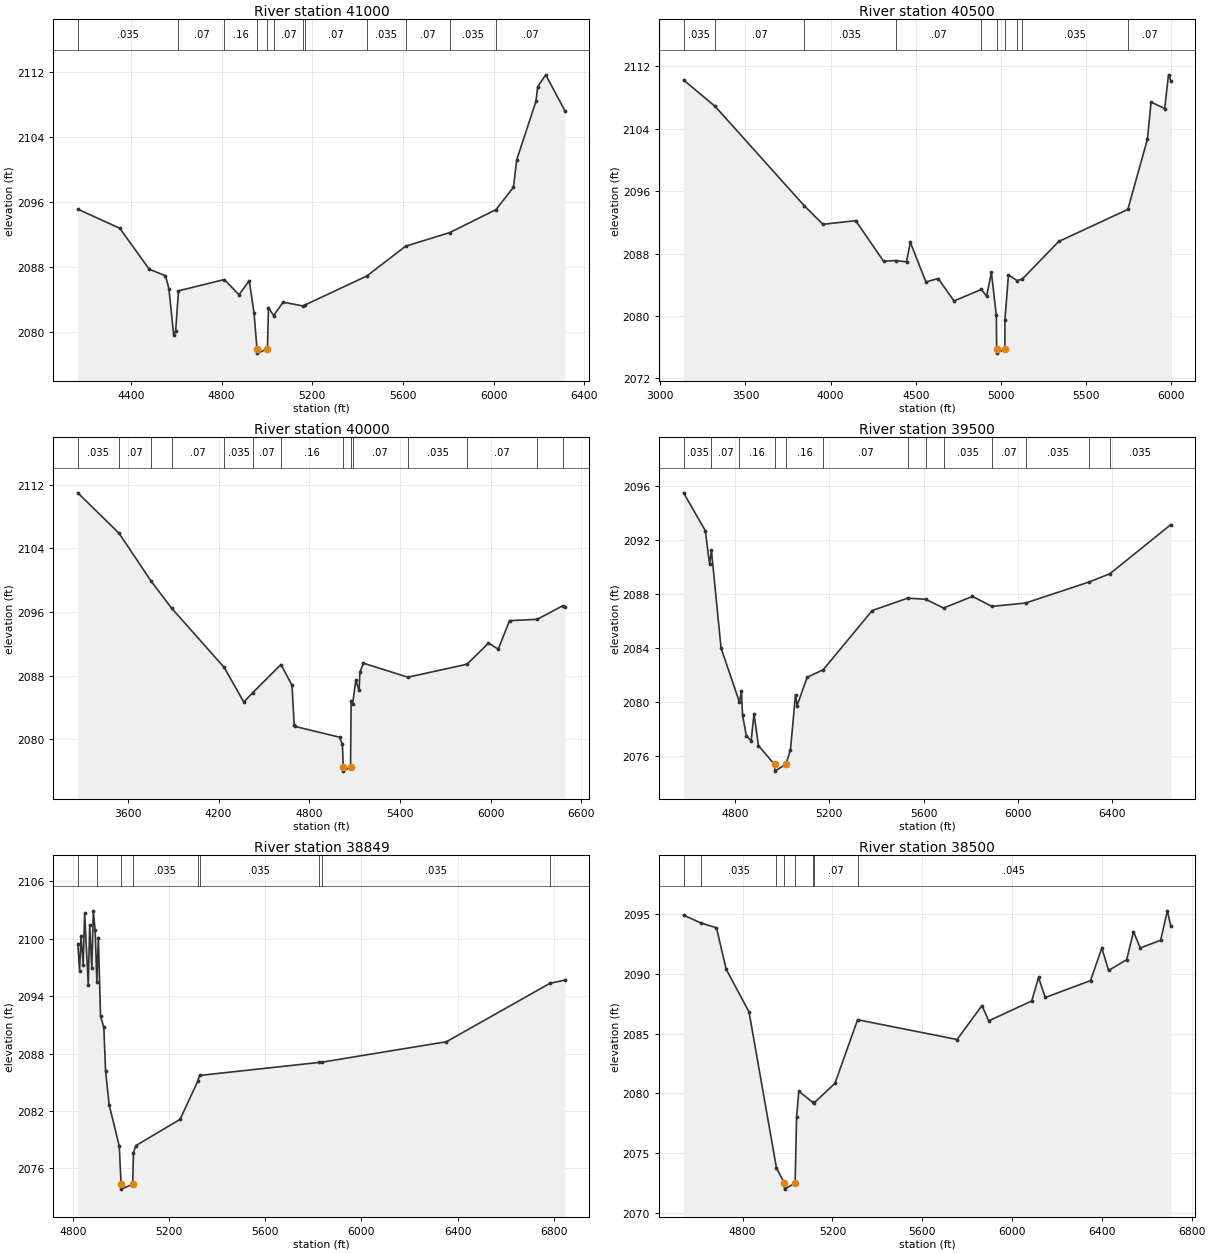
Type RM Length L Ch R = 1,41000,500,500,500
BEGIN DESCRIPTION:
Sweetwater Creek Trib 27 82.0
END DESCRIPTION:
XS GIS Cut Line= 3
      1379502.99      6878847.01      1379040.18      6878152.84
      1378205.01      6877138.02
#Sta/Elev= 30
  4165.7 2095.13  4351.1 2092.78  4480.3 2087.77  4552.4 2086.95  4567.4 2085.38
  4588.4 2079.73  4597.2 2080.14  4609.7 2085.10  4811.8 2086.49  4876.9 2084.62
  4921.7 2086.36  4943.0 2082.39  4955.9 2077.95  4956.9 2077.45  5002.1 2077.95
  5006.5 2083.05  5029.3 2082.06  5071.0 2083.71  5159.2 2083.24  5165.8 2083.34
  5440.1 2086.92  5611.1 2090.58  5805.4 2092.25  6009.7 2095.07  6086.9 2097.83
  6101.3 2101.21  6185.9 2108.36  6193.8 2110.18  6229.0 2111.63  6314.3 2107.19
#Mann=12,-1,0
  4165.7   0.035       0  4609.7    0.07       0  4811.8    0.16       0
  4955.9    0.07       0  5002.1    0.16       0  5029.3    0.07       0
  5159.2   0.035       0  5165.8    0.07       0  5440.1   0.035       0
  5611.1    0.07       0  5805.4   0.035       0  6009.7    0.07       0
Bank Sta=4955.9,5002.1
Exp/Cntr=0.3,0.1

Type RM Length L Ch R = 1,40500,500,500,500
BEGIN DESCRIPTION:
Sweetwater Creek Trib 27 81.0
END DESCRIPTION:
XS GIS Cut Line= 3
      1380605.01      6878888.01      1379139.24      6877736.65
      1378304.99      6877187.99
#Sta/Elev= 30
  3136.1 2110.26  3321.4 2106.88  3845.2 2094.14  3955.0 2091.75  4147.5 2092.22
  4311.1 2087.02  4382.4 2087.10  4445.9 2086.94  4468.3 2089.43  4560.3 2084.36
  4631.9 2084.80  4725.0 2081.92  4886.0 2083.40  4916.4 2082.52  4944.7 2085.57
  4973.6 2080.08  4975.5 2075.73  4976.5 2075.23  5023.5 2075.73  5023.9 2079.51
  5045.0 2085.26  5094.5 2084.54  5124.9 2084.70  5340.2 2089.55  5746.1 2093.66
  5861.4 2102.69  5882.5 2107.43  5962.6 2106.60  5985.0 2110.92  5998.5 2110.19
#Mann=10,-1,0
  3136.1   0.035       0  3321.4    0.07       0  3845.2   0.035       0
  4382.4    0.07       0  4886.0    0.16       0  4975.5    0.07       0
  5023.5    0.16       0  5094.5    0.07       0  5124.9   0.035       0
  5746.1    0.07       0
Bank Sta=4975.5,5023.5
Exp/Cntr=0.3,0.1

Type RM Length L Ch R = 1,40000,500,500,500
BEGIN DESCRIPTION:
Sweetwater Creek Trib 27 80.0
END DESCRIPTION:
XS GIS Cut Line= 3
      1380654.98      6878837.97      1379511.24      6877537.99
      1378221.44      6876789.00
#Sta/Elev= 30
  3268.5 2110.96  3541.7 2105.88  3754.6 2099.84  3888.8 2096.48  4237.1 2089.02
  4366.7 2084.68  4426.3 2085.87  4612.7 2089.39  4685.5 2086.79  4699.7 2081.85
  4707.0 2081.61  5000.0 2080.26  5018.8 2079.37  5024.7 2076.50  5025.7 2076.00
  5072.7 2076.50  5076.6 2084.86  5087.1 2084.49  5107.5 2087.42  5129.0 2086.13
  5134.8 2088.42  5157.5 2089.56  5452.0 2087.80  5843.4 2089.43  5985.0 2092.08
  6049.6 2091.33  6124.1 2094.90  6307.4 2095.07  6475.4 2096.76  6491.5 2096.67
#Mann=14,-1,0
  3268.5   0.035       0  3541.7    0.07       0  3754.6    0.16       0
  3888.8    0.07       0  4237.1   0.035       0  4426.3    0.07       0
  4612.7    0.16       0  5024.7    0.07       0  5072.7    0.16       0
  5087.1    0.07       0  5452.0   0.035       0  5843.4    0.07       0
  6307.4   0.035       0  6475.4    0.07       0
Bank Sta=5024.7,5072.7
Exp/Cntr=0.3,0.1

Type RM Length L Ch R = 1,39500,651,651,651
BEGIN DESCRIPTION:
Sweetwater Creek Trib 27 79.0
END DESCRIPTION:
XS GIS Cut Line= 4
      1380355.03      6877738.01      1379946.57      6877645.99
      1379444.85      6877179.52      1378522.69      6876897.79
#Sta/Elev= 30
  4581.3 2095.51  4673.6 2092.71  4692.0 2090.20  4699.6 2091.25  4740.4 2084.00
  4818.7 2079.97  4826.9 2080.80  4832.0 2078.99  4847.8 2077.47  4868.3 2077.09
  4880.4 2079.12  4899.1 2076.75  4967.4 2075.35  4968.4 2074.85  5015.4 2075.35
  5035.0 2076.41  5056.5 2080.52  5063.4 2079.72  5105.9 2081.82  5174.4 2082.38
  5381.9 2086.77  5532.0 2087.69  5608.3 2087.61  5684.9 2086.96  5807.6 2087.82
  5890.2 2087.08  6033.0 2087.33  6303.8 2088.90  6390.6 2089.50  6649.3 2093.15
#Mann=13,-1,0
  4581.3   0.035       0  4699.6    0.07       0  4818.7    0.16       0
  4967.4    0.07       0  5015.4    0.16       0  5174.4    0.07       0
  5532.0   0.035       0  5608.3    0.07       0  5684.9   0.035       0
  5890.2    0.07       0  6033.0   0.035       0  6303.8    0.07       0
  6390.6   0.035       0
Bank Sta=4967.4,5015.4
Exp/Cntr=0.3,0.1

Type RM Length L Ch R = 1,38849,349,349,349
BEGIN DESCRIPTION:
Sweetwater Creek Trib 27 78.0
END DESCRIPTION:
XS GIS Cut Line= 3
      1380205.02      6877288.01      1380055.33      6877187.86
      1378253.59      6876781.49
#Sta/Elev= 30
  4819.9 2099.47  4827.4 2096.66  4833.4 2100.24  4842.4 2097.29  4848.4 2102.66
  4863.5 2095.19  4869.5 2101.38  4878.5 2096.92  4884.5 2102.90  4892.1 2100.90
  4899.2 2095.52  4905.5 2100.11  4914.5 2091.93  4928.2 2090.73  4935.5 2086.21
  4950.5 2082.64  4992.6 2078.32  5000.0 2074.34  5001.0 2073.84  5048.1 2074.34
  5051.6 2077.66  5061.8 2078.39  5245.3 2081.12  5319.4 2085.13  5326.5 2085.71
  5823.6 2087.07  5833.9 2087.09  6353.5 2089.23  6784.0 2095.33  6847.0 2095.67
#Mann=9,-1,0
  4819.9    0.07       0  4899.2   0.035       0  5000.0   0.035       0
  5048.1   0.035       0  5319.4    0.07       0  5326.5   0.035       0
  5823.6    0.07       0  5833.9   0.035       0  6784.0    0.07       0
Bank Sta=5000,5048.1
Exp/Cntr=0.3,0.1

Type RM Length L Ch R = 1,38500,500,500,500
BEGIN DESCRIPTION:
Sweetwater Creek Trib 27 77.0
END DESCRIPTION:
XS GIS Cut Line= 3
      1380405.04      6877088.02      1380004.98      6876854.75
      1378309.93      6876652.33
#Sta/Elev= 30
  4536.9 2094.89  4612.5 2094.25  4683.7 2093.83  4726.7 2090.37  4828.5 2086.81
  4950.7 2073.78  4985.8 2072.50  4986.8 2072.00  5033.9 2072.50  5040.3 2077.99
  5050.3 2080.18  5111.5 2079.26  5118.6 2079.21  5211.5 2080.84  5312.0 2086.15
  5755.3 2084.50  5866.1 2087.34  5896.3 2086.06  6087.7 2087.72  6117.9 2089.68
  6148.1 2088.01  6349.5 2089.42  6399.9 2092.14  6430.1 2090.27  6510.6 2091.17
  6540.9 2093.51  6571.1 2092.15  6661.7 2092.79  6691.9 2095.25  6707.1 2093.97
#Mann=8,-1,0
  4536.9    0.07       0  4612.5   0.035       0  4950.7    0.07       0
  4985.8    0.07       0  5033.9    0.07       0  5111.5    0.16       0
  5118.6    0.07       0  5312.0   0.045       0
Bank Sta=4985.8,5033.9
Exp/Cntr=0.3,0.1

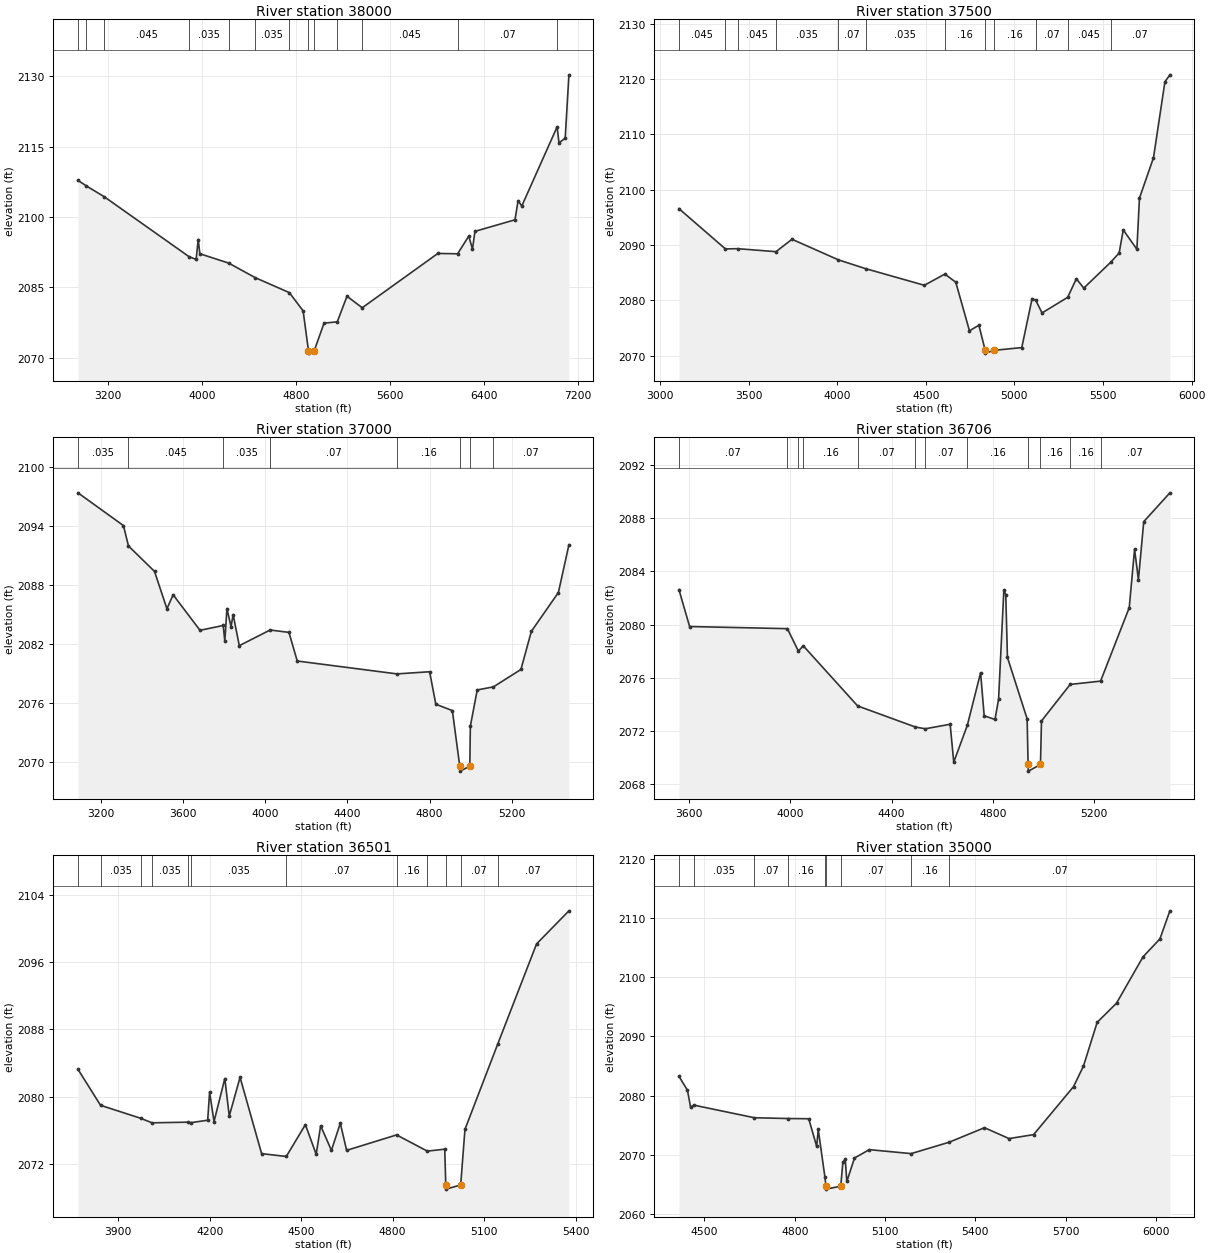
Type RM Length L Ch R = 1,38000,500,500,500
BEGIN DESCRIPTION:
Sweetwater Creek Trib 27 76.0
END DESCRIPTION:
XS GIS Cut Line= 3
      1381805.02      6877238.01      1379923.52      6876407.10
      1377905.03      6875738.01
#Sta/Elev= 30
  2943.2 2107.81  3015.3 2106.62  3166.1 2104.34  3889.5 2091.56  3950.1 2090.97
  3967.9 2095.21  3981.7 2092.18  4227.7 2090.18  4455.5 2087.06  4744.5 2083.89
  4861.7 2080.01  4907.3 2071.50  4908.3 2071.00  4956.0 2071.50  5040.1 2077.39
  5152.7 2077.67  5235.5 2083.12  5365.4 2080.67  6009.8 2092.24  6178.1 2092.17
  6273.2 2095.94  6304.8 2093.17  6325.9 2096.95  6667.0 2099.41  6693.4 2103.47
  6725.1 2102.36  7026.0 2119.22  7042.0 2115.78  7094.9 2116.82  7126.5 2130.30
#Mann=13,-1,0
  2943.2    0.07       0  3015.3   0.035       0  3166.1   0.045       0
  3889.5   0.035       0  4227.7    0.07       0  4455.5   0.035       0
  4744.5    0.07       0  4907.3    0.07       0  4956.0    0.07       0
  5152.7    0.07       0  5365.4   0.045       0  6178.1    0.07       0
  7026.0   0.063       0
Bank Sta=4907.3,4956
Exp/Cntr=0.3,0.1

Type RM Length L Ch R = 1,37500,500,500,500
BEGIN DESCRIPTION:
Sweetwater Creek Trib 27 75.0
END DESCRIPTION:
XS GIS Cut Line= 3
      1381454.97      6876737.99      1379705.23      6876016.36
      1379005.01      6875488.00
#Sta/Elev= 30
  3107.3 2096.58  3369.3 2089.31  3438.2 2089.35  3654.9 2088.81  3745.0 2091.05
  4007.1 2087.33  4160.9 2085.74  4491.8 2082.74  4607.5 2084.76  4669.1 2083.30
  4746.3 2074.53  4799.6 2075.52  4835.2 2070.99  4836.2 2070.49  4884.1 2070.99
  5041.5 2071.49  5099.7 2080.33  5120.3 2080.04  5155.9 2077.75  5300.3 2080.56
  5349.5 2083.92  5391.2 2082.23  5542.6 2086.88  5591.0 2088.58  5613.9 2092.74
  5690.9 2089.25  5705.5 2098.48  5784.6 2105.77  5849.1 2119.48  5877.2 2120.74
#Mann=12,-1,0
  3107.3   0.045       0  3369.3   0.035       0  3438.2   0.045       0
  3654.9   0.035       0  4007.1    0.07       0  4160.9   0.035       0
  4607.5    0.16       0  4835.2    0.07       0  4884.1    0.16       0
  5120.3    0.07       0  5300.3   0.045       0  5542.6    0.07       0
Bank Sta=4835.2,4884.1
Exp/Cntr=0.3,0.1

Type RM Length L Ch R = 1,37000,294,294,294
BEGIN DESCRIPTION:
Sweetwater Creek Trib 27 74.0
END DESCRIPTION:
XS GIS Cut Line= 3
      1381605.03      6875338.00      1379706.13      6875549.10
      1379234.41      6875623.14
#Sta/Elev= 30
  3089.4 2097.33  3310.7 2094.00  3335.0 2091.93  3461.7 2089.35  3522.1 2085.55
  3552.3 2086.97  3683.1 2083.36  3795.8 2083.85  3803.8 2082.24  3813.9 2085.57
  3834.0 2083.73  3844.1 2084.96  3874.2 2081.80  4023.9 2083.39  4115.7 2083.15
  4156.0 2080.24  4641.4 2078.93  4799.9 2079.15  4830.1 2075.85  4910.6 2075.20
  4946.5 2069.55  4947.5 2069.05  4995.4 2069.55  4998.1 2073.62  5031.5 2077.30
  5110.0 2077.61  5244.1 2079.38  5294.7 2083.25  5426.3 2087.20  5477.5 2092.05
#Mann=8,-1,0
  3089.4   0.035       0  3335.0   0.045       0  3795.8   0.035       0
  4023.9    0.07       0  4641.4    0.16       0  4946.5    0.07       0
  4995.4    0.16       0  5110.0    0.07       0
Bank Sta=4946.5,4995.4
Exp/Cntr=0.3,0.1

Type RM Length L Ch R = 1,36706,205,205,205
BEGIN DESCRIPTION:
Sweetwater Creek Trib 27 73.0
END DESCRIPTION:
XS GIS Cut Line= 4
      1380876.87      6874730.90      1380408.10      6874673.61
      1379685.12      6875318.09      1379264.86      6875590.28
#Sta/Elev= 30
  3559.2 2082.63  3601.4 2079.85  3988.0 2079.69  4031.5 2078.00  4050.8 2078.40
  4265.9 2073.87  4494.5 2072.28  4533.5 2072.15  4631.7 2072.49  4645.9 2069.64
  4699.5 2072.40  4752.1 2076.37  4766.3 2073.13  4809.0 2072.85  4823.2 2074.37
  4844.1 2082.61  4851.6 2082.26  4858.3 2077.52  4936.1 2072.90  4940.0 2069.46
  4941.0 2068.96  4988.9 2069.46  4992.9 2072.74  5106.4 2075.49  5226.6 2075.74
  5339.9 2081.27  5361.0 2085.67  5376.2 2083.38  5397.3 2087.75  5500.7 2089.92
#Mann=12,-1,0
  3559.2    0.07       0  3988.0    0.16       0  4031.5    0.07       0
  4050.8    0.16       0  4265.9    0.07       0  4494.5    0.16       0
  4533.5    0.07       0  4699.5    0.16       0  4940.0    0.07       0
  4988.9    0.16       0  5106.4    0.16       0  5226.6    0.07       0
Bank Sta=4940,4988.9
Exp/Cntr=0.3,0.1

Type RM Length L Ch R = 1,36501,1501,1501,1501
BEGIN DESCRIPTION:
Sweetwater Creek Trib 27 72.0
END DESCRIPTION:
XS GIS Cut Line= 4
      1380527.91      6874514.75      1380405.49      6874538.19
      1379517.53      6875209.03      1379178.56      6875364.39
#Sta/Elev= 30
  3767.9 2083.25  3841.9 2078.96  3973.7 2077.41  4011.1 2076.87  4130.4 2076.95
  4138.0 2076.89  4193.4 2077.18  4199.7 2080.53  4214.2 2077.02  4249.6 2082.15
  4264.2 2077.68  4299.6 2082.29  4370.3 2073.20  4451.2 2072.86  4513.9 2076.65
  4549.3 2073.12  4563.9 2076.52  4599.3 2073.59  4628.4 2076.82  4649.2 2073.59
  4813.0 2075.43  4913.8 2073.50  4971.0 2073.73  4974.4 2069.47  4975.4 2068.97
  5023.3 2069.47  5037.3 2076.09  5144.5 2086.23  5272.2 2098.19  5378.3 2102.13
#Mann=12,-1,0
  3767.9    0.07       0  3841.9   0.035       0  3973.7    0.07       0
  4011.1   0.035       0  4130.4    0.16       0  4138.0   0.035       0
  4451.2    0.07       0  4813.0    0.16       0  4913.8    0.07       0
  4974.4    0.07       0  5023.3    0.07       0  5144.5    0.07       0
Bank Sta=4974.4,5023.3
Exp/Cntr=0.3,0.1

Type RM Length L Ch R = 1,35000,1000,1000,1000
BEGIN DESCRIPTION:
Sweetwater Creek Trib 27 70.0
END DESCRIPTION:
XS GIS Cut Line= 3
      1380561.74      6874478.29      1380006.96      6874293.67
      1378981.16      6874500.29
#Sta/Elev= 30
  4415.3 2083.25  4443.5 2080.91  4454.0 2078.03  4464.9 2078.38  4666.1 2076.25
  4776.6 2076.12  4846.5 2076.08  4872.9 2071.41  4878.1 2074.27  4900.1 2066.29
  4903.8 2064.69  4904.8 2064.19  4952.8 2064.69  4959.9 2068.71  4967.8 2069.24
  4973.1 2065.48  4998.4 2069.44  5047.6 2070.86  5186.8 2070.19  5312.7 2072.11
  5430.4 2074.57  5512.0 2072.73  5593.6 2073.40  5726.3 2081.51  5759.1 2084.96
  5804.8 2092.37  5869.1 2095.61  5957.3 2103.45  6013.2 2106.46  6046.4 2111.21
#Mann=9,-1,0
  4415.3    0.07       0  4464.9   0.035       0  4666.1    0.07       0
  4776.6    0.16       0  4900.1    0.07       0  4903.8    0.07       0
  4952.8    0.07       0  5186.8    0.16       0  5312.7    0.07       0
Bank Sta=4903.8,4952.8
Exp/Cntr=0.3,0.1

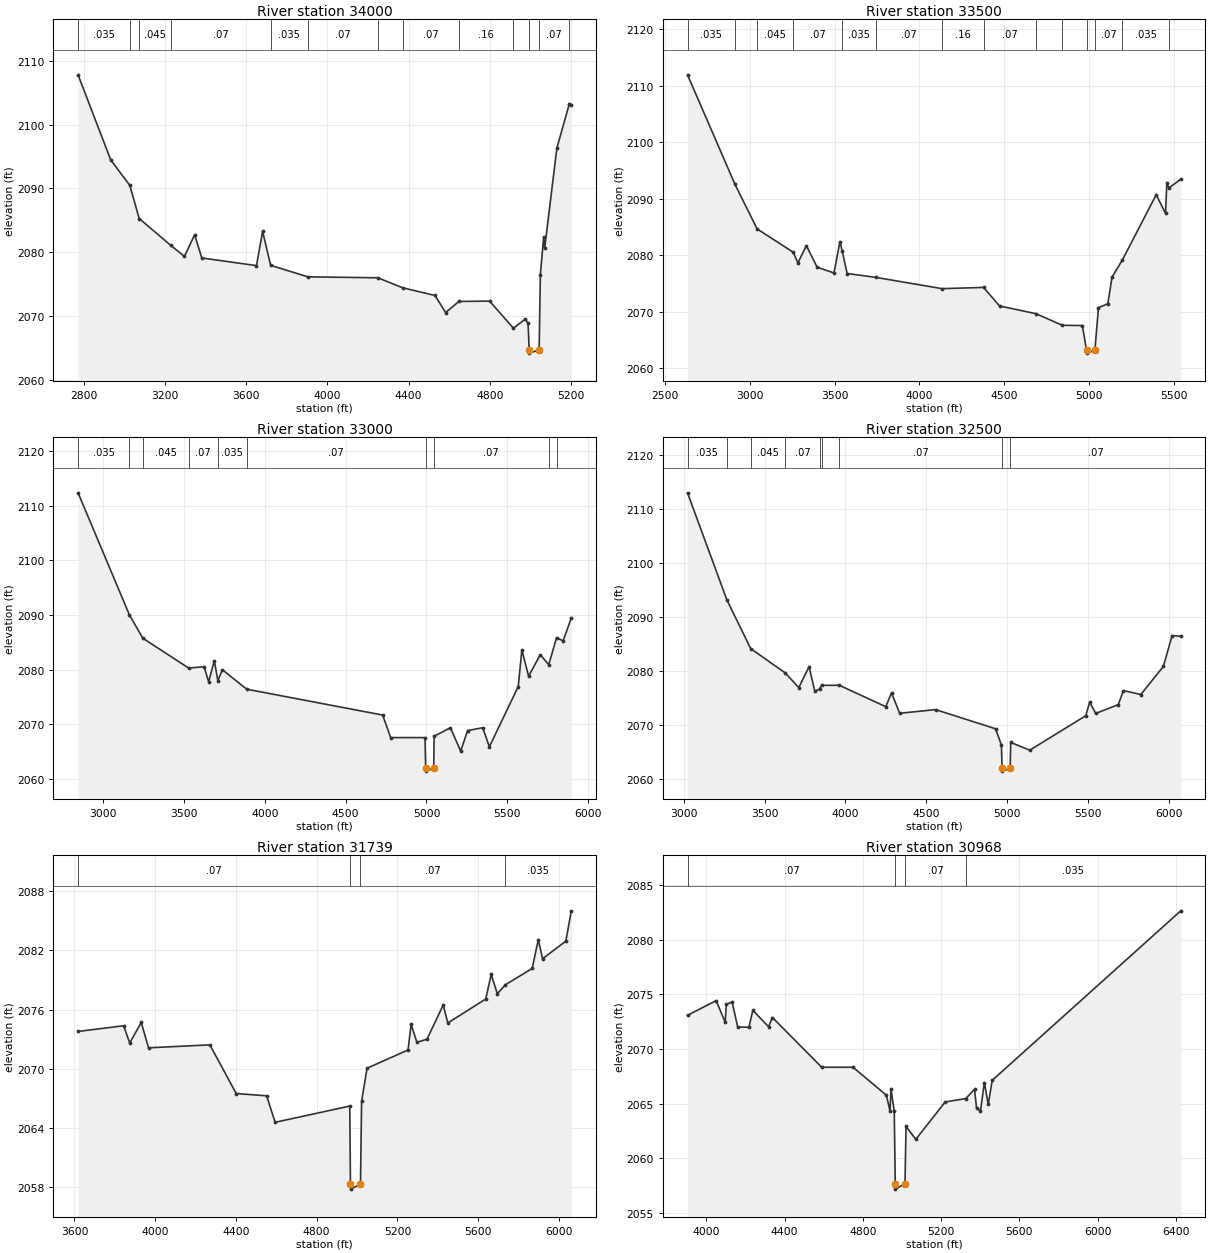
Type RM Length L Ch R = 1,34000,500,500,500
BEGIN DESCRIPTION:
Sweetwater Creek Trib 27 68.0
END DESCRIPTION:
XS GIS Cut Line= 3
      1381354.99      6874937.99      1379453.64      6873775.25
      1379255.00      6873738.00
#Sta/Elev= 30
  2771.3 2107.80  2931.9 2094.48  3026.2 2090.47  3072.5 2085.27  3227.1 2081.09
  3295.6 2079.33  3345.6 2082.73  3380.9 2079.09  3650.4 2077.89  3680.7 2083.26
  3720.3 2077.93  3903.9 2076.13  4248.7 2075.98  4371.4 2074.41  4530.3 2073.21
  4582.5 2070.53  4648.0 2072.27  4799.2 2072.33  4916.8 2068.08  4975.0 2069.51
  4988.8 2068.86  4994.5 2064.67  4995.5 2064.17  5043.5 2064.67  5049.5 2076.47
  5065.6 2082.32  5070.7 2080.62  5130.9 2096.32  5192.6 2103.29  5202.1 2103.11
#Mann=13,-1,0
  2771.3   0.035       0  3026.2    0.07       0  3072.5   0.045       0
  3227.1    0.07       0  3720.3   0.035       0  3903.9    0.07       0
  4248.7    0.16       0  4371.4    0.07       0  4648.0    0.16       0
  4916.8    0.07       0  4994.5    0.07       0  5043.5    0.07       0
  5192.6   0.035       0
Bank Sta=4994.5,5043.5
Exp/Cntr=0.3,0.1

Type RM Length L Ch R = 1,33500,500,500,500
BEGIN DESCRIPTION:
Sweetwater Creek Trib 27 67.0
END DESCRIPTION:
XS GIS Cut Line= 3
      1381405.02      6874938.02      1379655.02      6873343.78
      1379148.46      6873535.69
#Sta/Elev= 30
  2632.7 2111.89  2912.9 2092.51  3043.4 2084.64  3256.0 2080.53  3283.7 2078.63
  3333.7 2081.68  3397.2 2077.88  3496.6 2076.85  3531.7 2082.41  3544.7 2080.77
  3574.3 2076.76  3742.7 2076.08  4133.7 2074.08  4378.7 2074.30  4472.9 2071.02
  4688.3 2069.65  4843.3 2067.60  4961.4 2067.56  4986.2 2063.18  4987.2 2062.68
  5035.2 2063.18  5056.5 2070.73  5111.5 2071.40  5136.3 2076.10  5196.5 2079.10
  5397.0 2090.69  5452.0 2087.38  5459.8 2092.84  5471.4 2091.87  5541.7 2093.43
#Mann=14,-1,0
  2632.7   0.035       0  2912.9    0.07       0  3043.4   0.045       0
  3256.0    0.07       0  3544.7   0.035       0  3742.7    0.07       0
  4133.7    0.16       0  4378.7    0.07       0  4688.3    0.16       0
  4843.3    0.07       0  4986.2    0.07       0  5035.2    0.07       0
  5196.5   0.035       0  5471.4    0.07       0
Bank Sta=4986.2,5035.2
Exp/Cntr=0.3,0.1

Type RM Length L Ch R = 1,33000,500,500,500
BEGIN DESCRIPTION:
Sweetwater Creek Trib 27 66.0
END DESCRIPTION:
XS GIS Cut Line= 3
      1381505.02      6874788.02      1380062.00      6873188.43
      1379355.00      6872638.00
#Sta/Elev= 30
  2845.7 2112.36  3162.7 2090.03  3246.1 2085.73  3529.3 2080.27  3624.8 2080.51
  3653.2 2077.75  3688.3 2081.63  3709.9 2077.95  3737.7 2079.96  3889.2 2076.39
  4729.4 2071.66  4778.7 2067.53  4991.0 2067.53  4995.4 2061.89  4996.4 2061.39
  5044.9 2061.89  5047.3 2067.77  5148.3 2069.34  5211.6 2065.05  5254.5 2068.81
  5347.7 2069.34  5389.3 2065.86  5567.6 2076.88  5590.2 2083.59  5631.8 2078.78
  5704.2 2082.71  5756.3 2080.88  5804.9 2085.85  5845.3 2085.24  5896.0 2089.48
#Mann=10,-1,0
  2845.7   0.035       0  3162.7    0.07       0  3246.1   0.045       0
  3529.3    0.07       0  3709.9   0.035       0  3889.2    0.07       0
  4995.4    0.07       0  5044.9    0.07       0  5756.3   0.035       0
  5804.9    0.07       0
Bank Sta=4995.4,5044.9
Exp/Cntr=0.3,0.1

Type RM Length L Ch R = 1,32500,761,761,761
BEGIN DESCRIPTION:
Sweetwater Creek Trib 27 65.0
END DESCRIPTION:
XS GIS Cut Line= 3
      1381605.01      6874588.02      1380455.37      6872979.52
      1379454.96      6872587.99
#Sta/Elev= 30
  3022.9 2112.98  3266.1 2093.20  3413.8 2084.17  3628.6 2079.64  3711.2 2076.95
  3774.9 2080.83  3810.6 2076.26  3839.5 2076.70  3852.0 2077.37  3962.3 2077.38
  4249.2 2073.42  4284.9 2075.98  4335.3 2072.20  4557.7 2072.88  4928.8 2069.33
  4965.0 2066.30  4969.0 2062.00  4970.0 2061.50  5018.7 2062.00  5022.6 2066.81
  5140.0 2065.37  5486.7 2071.75  5511.1 2074.28  5548.1 2072.17  5687.7 2073.80
  5719.9 2076.40  5827.3 2075.67  5966.9 2080.87  6020.6 2086.57  6074.3 2086.46
#Mann=9,-1,0
  3022.9   0.035       0  3266.1    0.07       0  3413.8   0.045       0
  3628.6    0.07       0  3839.5   0.094       0  3852.0   0.035       0
  3962.3    0.07       0  4969.0    0.07       0  5018.7    0.07       0
Bank Sta=4969,5018.7
Exp/Cntr=0.3,0.1

Type RM Length L Ch R = 1,31739,771,771,771
BEGIN DESCRIPTION:
Sweetwater Creek Trib 27 64.0
END DESCRIPTION:
XS GIS Cut Line= 3
      1381041.83      6873464.33      1380284.87      6872307.96
      1379389.94      6871736.34
#Sta/Elev= 30
  3617.9 2073.78  3843.5 2074.36  3873.7 2072.61  3930.9 2074.69  3967.1 2072.12
  4270.9 2072.42  4401.4 2067.48  4552.1 2067.25  4594.3 2064.56  4964.1 2066.21
  4967.5 2058.28  4968.5 2057.78  5017.2 2058.28  5022.7 2066.69  5049.8 2070.05
  5252.8 2071.90  5268.1 2074.51  5296.5 2072.68  5346.7 2072.99  5427.0 2076.46
  5449.9 2074.64  5637.7 2077.07  5664.8 2079.56  5695.3 2077.60  5734.4 2078.51
  5867.9 2080.17  5898.3 2083.10  5919.5 2081.16  6034.5 2082.94  6061.9 2086.02
#Mann=4,-1,0
  3617.9    0.07       0  4967.5    0.07       0  5017.2    0.07       0
  5734.4   0.035       0
Bank Sta=4967.5,5017.2
Exp/Cntr=0.3,0.1

Type RM Length L Ch R = 1,30968,219,219,219
BEGIN DESCRIPTION:
Sweetwater Creek Trib 27 63.0
END DESCRIPTION:
XS GIS Cut Line= 4
      1380992.32      6873313.24      1380854.89      6873086.02
      1380785.16      6872258.60      1380836.79      6870835.14
#Sta/Elev= 30
  3904.1 2073.09  4050.5 2074.44  4096.6 2072.46  4102.4 2074.10  4132.3 2074.31
  4160.6 2072.02  4217.8 2072.00  4237.9 2073.55  4318.2 2072.05  4338.3 2072.89
  4589.7 2068.34  4749.7 2068.34  4920.3 2065.78  4938.9 2064.32  4943.9 2066.32
  4960.5 2064.32  4965.7 2057.68  4966.7 2057.18  5015.5 2057.68  5020.6 2062.93
  5070.6 2061.74  5220.7 2065.16  5325.8 2065.47  5370.8 2066.32  5380.9 2064.62
  5400.9 2064.33  5420.9 2066.94  5440.9 2064.93  5460.9 2067.14  6424.4 2082.66
#Mann=4,-1,0
  3904.1    0.07       0  4965.7    0.07       0  5015.5    0.07       0
  5325.8   0.035       0
Bank Sta=4965.7,5015.5
Exp/Cntr=0.3,0.1

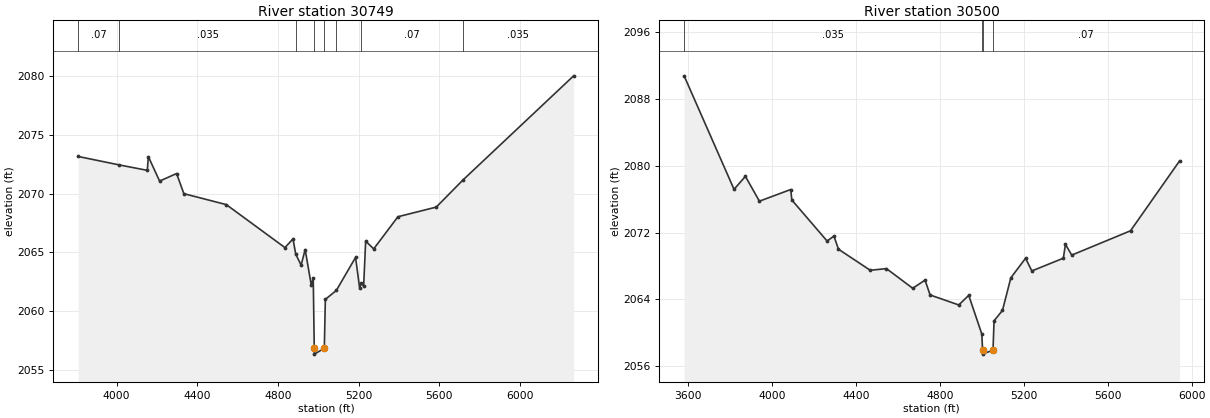
Type RM Length L Ch R = 1,30749,249,249,249
BEGIN DESCRIPTION:
Sweetwater Creek Trib 27 62.0
END DESCRIPTION:
XS GIS Cut Line= 3
      1381024.78      6873290.79      1380939.78      6872103.23
      1380952.14      6870836.59
#Sta/Elev= 30
  3809.4 2073.15  4013.6 2072.43  4152.3 2071.97  4157.3 2073.14  4213.2 2071.06
  4297.5 2071.70  4333.5 2069.99  4544.1 2069.06  4834.8 2065.41  4874.9 2066.15
  4888.2 2064.86  4915.0 2063.92  4935.1 2065.24  4965.1 2062.26  4975.2 2062.80
  4980.3 2056.86  4981.3 2056.36  5030.2 2056.86  5035.2 2061.01  5089.8 2061.77
  5185.2 2064.58  5205.2 2061.98  5213.9 2062.39  5225.2 2062.14  5235.2 2065.96
  5275.2 2065.30  5395.2 2068.03  5585.3 2068.85  5717.7 2071.15  6266.7 2080.00
#Mann=8,-1,0
  3809.4    0.07       0  4013.6   0.035       0  4888.2    0.07       0
  4980.3    0.07       0  5030.2    0.07       0  5089.8   0.035       0
  5213.9    0.07       0  5717.7   0.035       0
Bank Sta=4980.3,5030.2
Exp/Cntr=0.3,0.1

Type RM Length L Ch R = 1,30500,500,500,500
BEGIN DESCRIPTION:
Sweetwater Creek Trib 27 61.0
END DESCRIPTION:
XS GIS Cut Line= 3
      1381654.99      6873237.98      1381116.02      6871926.94
      1381118.18      6870984.44
#Sta/Elev= 30
  3582.5 2090.80  3820.3 2077.18  3874.4 2078.74  3941.1 2075.76  4090.3 2077.16
  4095.7 2075.90  4263.6 2070.98  4296.1 2071.57  4317.7 2070.00  4469.1 2067.47
  4546.3 2067.67  4671.5 2065.31  4730.2 2066.29  4754.2 2064.51  4890.7 2063.31
  4938.2 2064.46  5000.8 2059.81  5004.0 2057.91  5005.0 2057.41  5053.9 2057.91
  5058.9 2061.41  5098.9 2062.65  5138.9 2066.57  5208.9 2068.91  5238.9 2067.39
  5388.9 2068.92  5398.9 2070.58  5428.9 2069.29  5708.9 2072.21  5942.5 2080.59
#Mann=4,-1,0
  3582.5   0.035       0  5000.8    0.07       0  5004.0   0.035       0
  5053.9    0.07       0
Bank Sta=5004,5053.9
Exp/Cntr=0.3,0.1