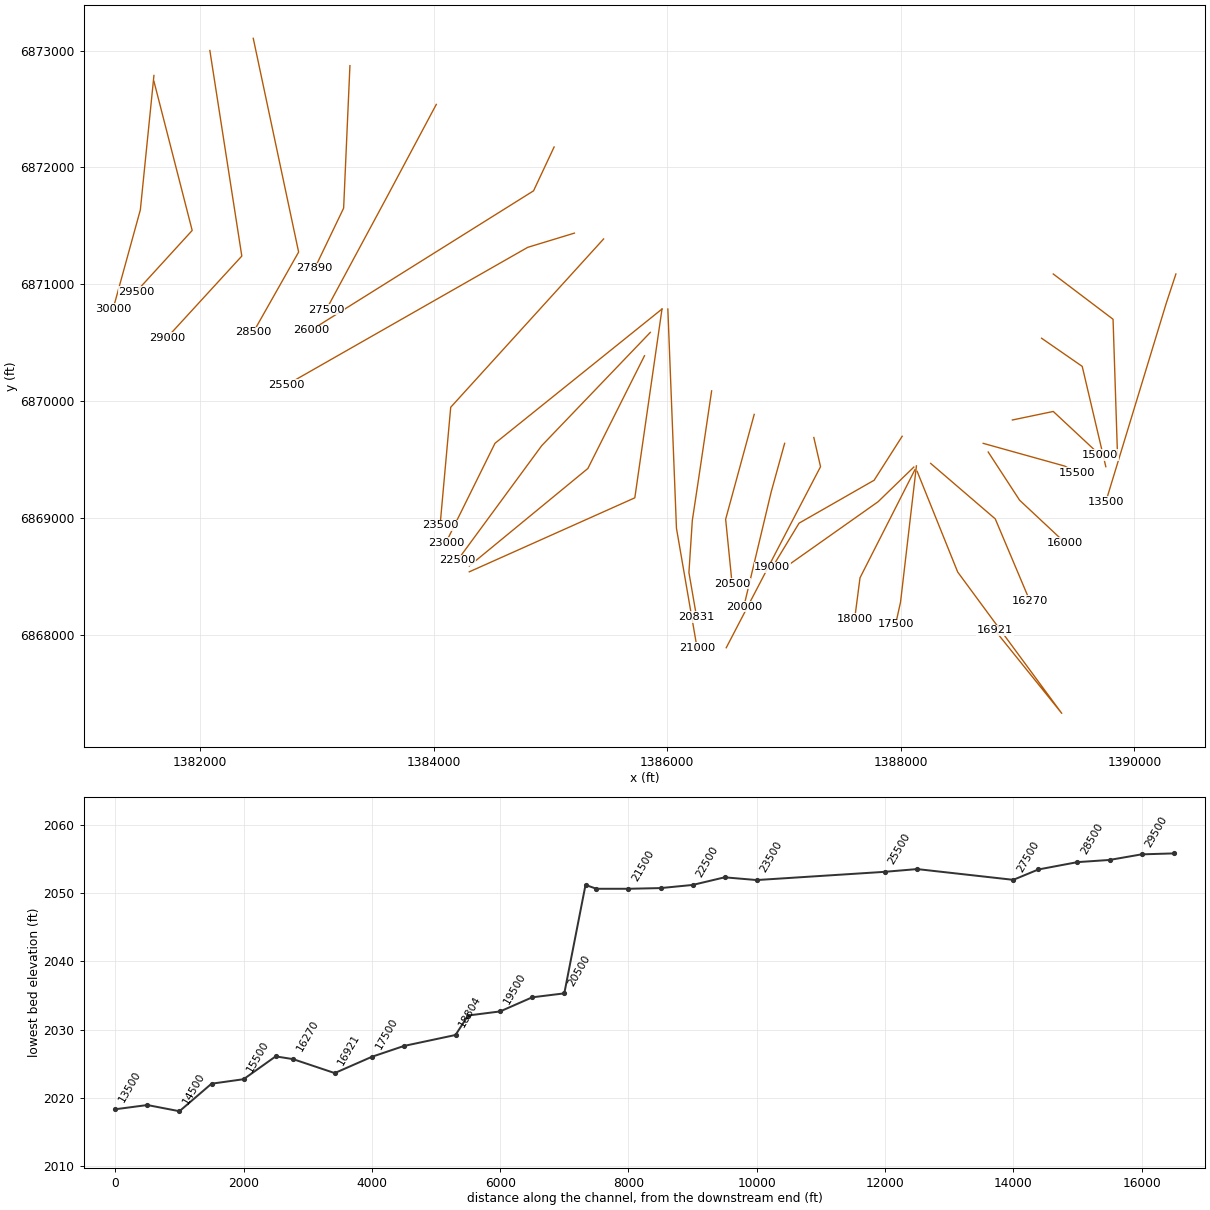
HEC-RAS study Sweetwater Creek Trib 27.prj: Sweetwater Creek Trib 27 Base Level Engineering

--- Sweetwater Creek Trib 27.g01 (geometry) --- (continued)

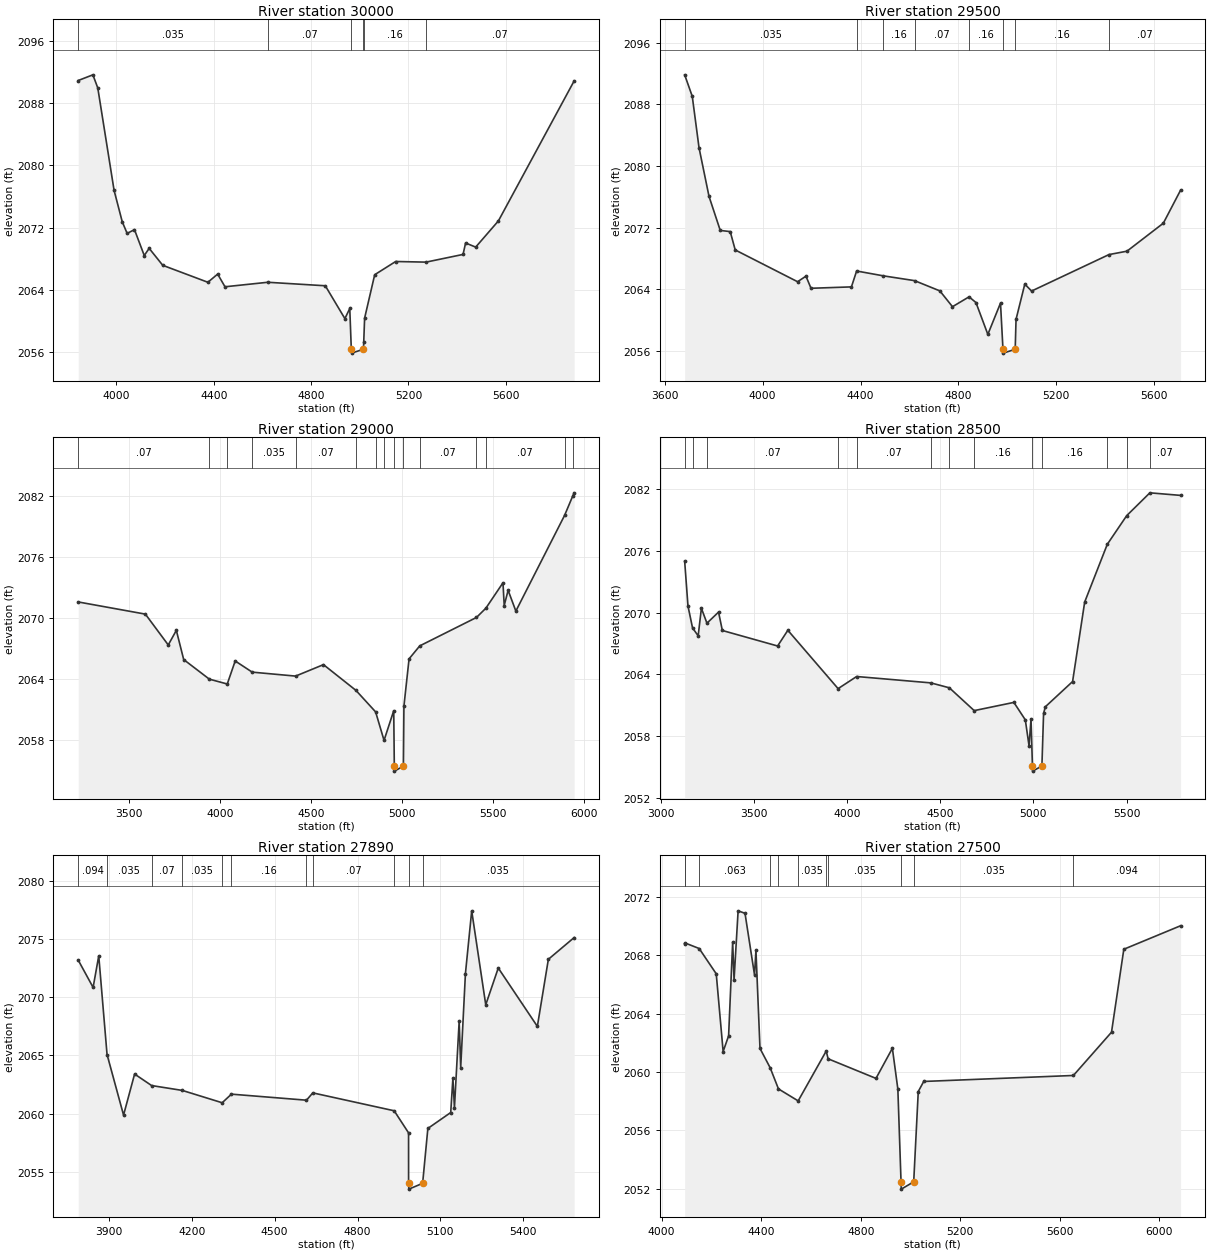
Type RM Length L Ch R = 1,30000,500,500,500
BEGIN DESCRIPTION:
Sweetwater Creek Trib 27 60.0
END DESCRIPTION:
XS GIS Cut Line= 3
      1381605.00      6872787.97      1381488.61      6871637.14
      1381255.00      6870787.99
#Sta/Elev= 30
  3843.3 2090.91  3903.6 2091.64  3923.7 2089.95  3990.7 2076.78  4024.2 2072.75
  4044.3 2071.25  4074.4 2071.74  4114.6 2068.41  4134.8 2069.33  4190.6 2067.15
  4376.0 2064.97  4416.2 2066.02  4446.3 2064.39  4622.1 2064.97  4858.4 2064.52
  4938.8 2060.30  4958.9 2061.60  4965.2 2056.36  4966.2 2055.86  5015.2 2056.36
  5016.3 2057.30  5019.9 2060.36  5061.3 2065.94  5147.5 2067.64  5272.3 2067.56
  5424.3 2068.55  5434.7 2070.02  5476.2 2069.49  5569.5 2072.86  5880.7 2090.86
#Mann=6,-1,0
  3843.3   0.035       0  4622.1    0.07       0  4965.2    0.07       0
  5015.2    0.07       0  5016.3    0.16       0  5272.3    0.07       0
Bank Sta=4965.2,5015.2
Exp/Cntr=0.3,0.1

Type RM Length L Ch R = 1,29500,500,500,500
BEGIN DESCRIPTION:
Sweetwater Creek Trib 27 59.0
END DESCRIPTION:
XS GIS Cut Line= 3
      1381604.99      6872738.04      1381932.41      6871460.84
      1381455.01      6870938.01
#Sta/Elev= 30
  3681.5 2091.81  3712.5 2089.02  3740.1 2082.36  3780.9 2076.05  3826.9 2071.63
  3867.6 2071.48  3888.0 2069.10  4142.8 2064.98  4177.1 2065.70  4197.7 2064.13
  4362.9 2064.31  4384.1 2066.37  4493.7 2065.74  4620.8 2065.12  4724.2 2063.79
  4775.8 2061.74  4843.5 2063.02  4871.7 2062.28  4920.3 2058.15  4972.0 2062.21
  4982.1 2056.22  4983.1 2055.72  5032.1 2056.22  5035.5 2060.10  5071.3 2064.67
  5099.0 2063.77  5415.3 2068.50  5488.8 2068.94  5637.4 2072.57  5708.0 2076.86
#Mann=8,-1,0
  3681.5   0.035       0  4384.1    0.07       0  4493.7    0.16       0
  4620.8    0.07       0  4843.5    0.16       0  4982.1    0.07       0
  5032.1    0.16       0  5415.3    0.07       0
Bank Sta=4982.1,5032.1
Exp/Cntr=0.3,0.1

Type RM Length L Ch R = 1,29000,500,500,500
BEGIN DESCRIPTION:
Sweetwater Creek Trib 27 58.0
END DESCRIPTION:
XS GIS Cut Line= 3
      1382083.72      6873001.63      1382357.34      6871241.48
      1381716.63      6870542.77
#Sta/Elev= 30
  3218.7 2071.58  3588.4 2070.38  3714.2 2067.34  3758.7 2068.78  3799.2 2065.90
  3940.2 2063.97  4038.9 2063.49  4082.6 2065.76  4176.2 2064.66  4415.0 2064.27
  4568.4 2065.40  4747.2 2062.86  4855.4 2060.74  4901.8 2057.93  4955.1 2060.86
  4958.3 2055.40  4959.3 2054.90  5008.3 2055.40  5011.2 2061.31  5039.5 2065.97
  5098.4 2067.25  5410.3 2070.05  5462.0 2070.96  5556.3 2073.47  5563.1 2071.23
  5584.6 2072.73  5627.2 2070.68  5895.2 2080.11  5940.3 2082.03  5948.0 2082.34
#Mann=15,-1,0
  3218.7    0.07       0  3940.2   0.035       0  4038.9    0.07       0
  4176.2   0.035       0  4415.0    0.07       0  4747.2    0.16       0
  4855.4    0.07       0  4901.8    0.16       0  4958.3    0.07       0
  5008.3    0.16       0  5098.4    0.07       0  5410.3    0.16       0
  5462.0    0.07       0  5895.2    0.16       0  5940.3    0.07       0
Bank Sta=4958.3,5008.3
Exp/Cntr=0.3,0.1

Type RM Length L Ch R = 1,28500,610,610,610
BEGIN DESCRIPTION:
Sweetwater Creek Trib 27 57.0
END DESCRIPTION:
XS GIS Cut Line= 3
      1382455.35      6873105.73      1382843.83      6871275.82
      1382455.01      6870588.01
#Sta/Elev= 30
  3129.3 2075.00  3147.0 2070.65  3171.5 2068.52  3201.7 2067.75  3219.0 2070.43
  3248.8 2068.98  3311.0 2070.06  3331.4 2068.27  3627.9 2066.76  3682.8 2068.29
  3952.4 2062.61  4051.9 2063.79  4449.9 2063.17  4549.4 2062.69  4682.6 2060.47
  4895.5 2061.27  4956.9 2059.57  4976.9 2057.04  4987.5 2059.66  4995.1 2055.08
  4996.1 2054.58  5045.9 2055.08  5054.9 2060.21  5064.7 2060.85  5210.5 2063.30
  5275.4 2071.04  5396.7 2076.66  5500.9 2079.45  5625.2 2081.67  5790.1 2081.42
#Mann=13,-1,0
  3129.3   0.094       0  3171.5   0.035       0  3248.8    0.07       0
  3952.4   0.035       0  4051.9    0.07       0  4449.9   0.035       0
  4549.4    0.07       0  4682.6    0.16       0  4995.1    0.07       0
  5045.9    0.16       0  5396.7    0.07       0  5500.9    0.16       0
  5625.2    0.07       0
Bank Sta=4995.1,5045.9
Exp/Cntr=0.3,0.1

Type RM Length L Ch R = 1,27890,390,390,390
BEGIN DESCRIPTION:
Sweetwater Creek Trib 27 56.0
END DESCRIPTION:
XS GIS Cut Line= 3
      1383283.07      6872871.83      1383229.21      6871652.05
      1382981.26      6871135.44
#Sta/Elev= 30
  3789.7 2073.20  3843.6 2070.85  3864.0 2073.57  3894.0 2065.08  3953.7 2059.87
  3993.7 2063.40  4055.2 2062.41  4166.4 2061.99  4310.5 2060.93  4343.9 2061.67
  4615.4 2061.15  4638.3 2061.78  4932.7 2060.24  4984.7 2058.34  4984.8 2054.00
  4985.8 2053.50  5035.6 2054.00  5054.5 2058.72  5137.2 2060.09  5145.1 2063.05
  5150.7 2060.51  5167.8 2067.96  5173.3 2063.96  5190.4 2072.04  5213.1 2077.44
  5263.9 2069.36  5309.2 2072.52  5450.6 2067.50  5490.4 2073.27  5583.7 2075.14
#Mann=11,-1,0
  3789.7   0.094       0  3894.0   0.035       0  4055.2    0.07       0
  4166.4   0.035       0  4310.5    0.07       0  4343.9    0.16       0
  4615.4   0.035       0  4638.3    0.07       0  4932.7   0.035       0
  4984.8   0.035       0  5035.6   0.035       0
Bank Sta=4984.8,5035.6
Exp/Cntr=0.3,0.1

Type RM Length L Ch R = 1,27500,1500,1500,1500
BEGIN DESCRIPTION:
Sweetwater Creek Trib 27 55.0
END DESCRIPTION:
XS GIS Cut Line= 3
      1384022.45      6872539.87      1383595.48      6871739.42
      1383080.97      6870783.72
#Sta/Elev= 30
  4092.8 2068.78  4095.8 2068.82  4151.1 2068.45  4219.6 2066.72  4247.3 2061.40
  4269.3 2062.47  4285.6 2068.89  4291.2 2066.31  4307.5 2071.03  4335.2 2070.86
  4373.4 2066.65  4379.1 2068.33  4395.4 2061.61  4436.2 2060.29  4469.6 2058.84
  4548.8 2058.02  4661.4 2061.43  4669.2 2060.90  4861.4 2059.56  4927.3 2061.62
  4949.3 2058.83  4962.1 2052.48  4963.1 2051.98  5013.0 2052.48  5031.3 2058.66
  5053.2 2059.35  5654.6 2059.76  5807.7 2062.72  5857.2 2068.40  6085.4 2070.01
#Mann=11,-1,0
  4092.8   0.094       0  4095.8   0.035       0  4151.1   0.063       0
  4436.2   0.035       0  4469.6   0.063       0  4548.8   0.035       0
  4661.4    0.07       0  4669.2   0.035       0  4962.1   0.035       0
  5013.0   0.035       0  5654.6   0.094       0
Bank Sta=4962.1,5013
Exp/Cntr=0.3,0.1

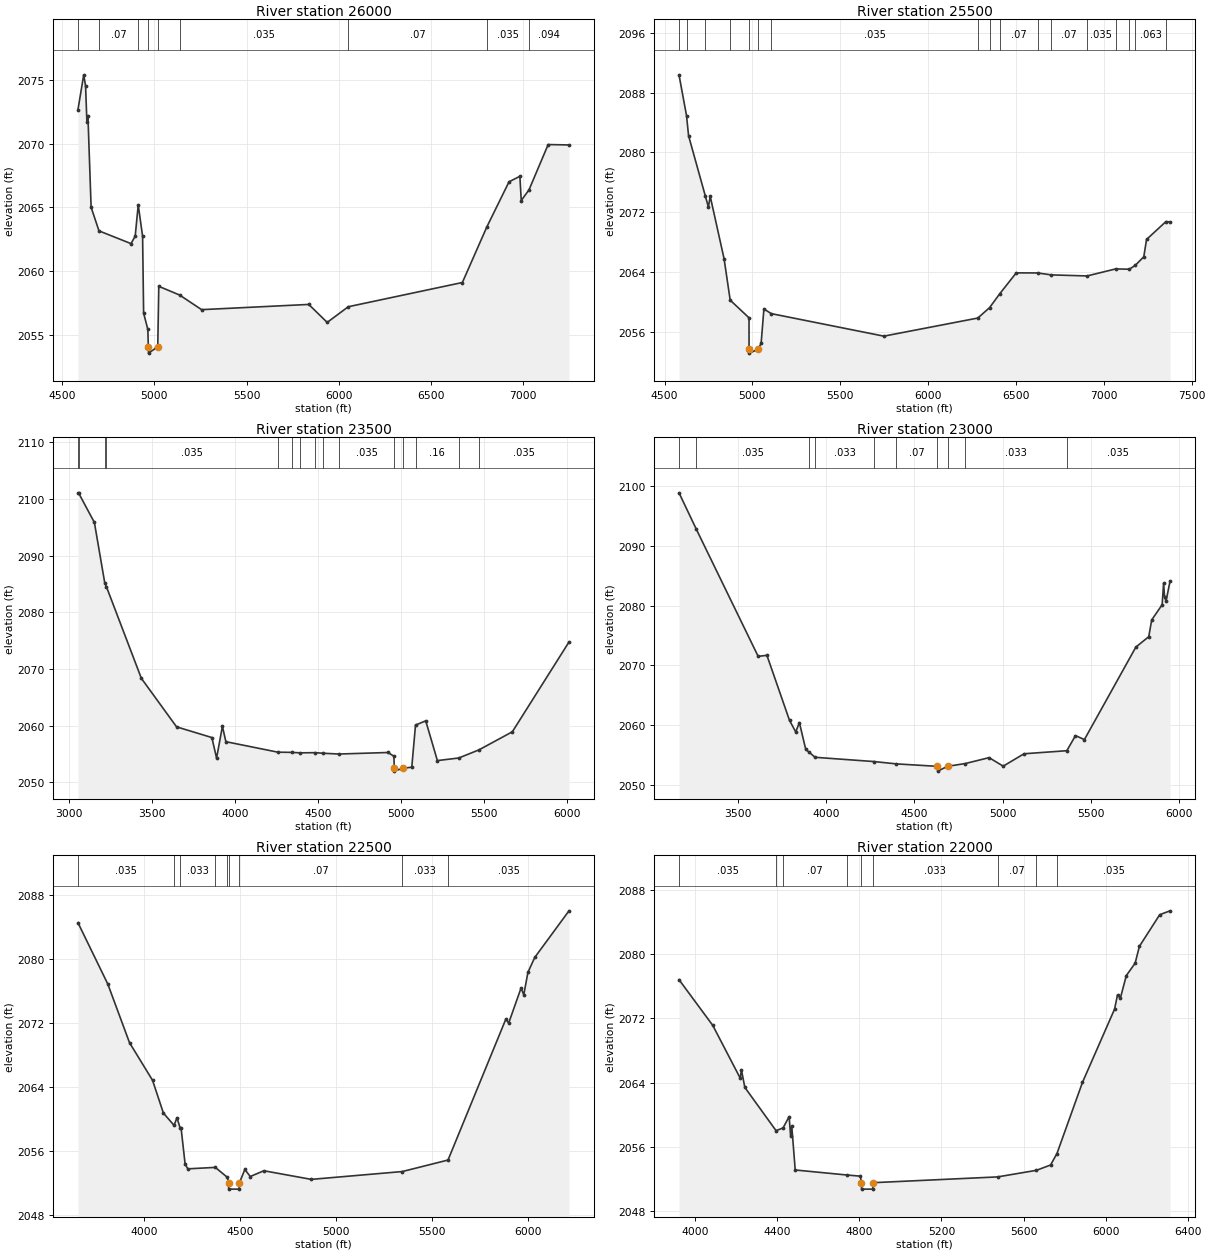
Type RM Length L Ch R = 1,26000,500,500,500
BEGIN DESCRIPTION:
Sweetwater Creek Trib 27 52.0
END DESCRIPTION:
XS GIS Cut Line= 3
      1385031.27      6872175.40      1384855.14      6871800.07
      1382949.35      6870606.50
#Sta/Elev= 30
  4585.4 2072.66  4616.6 2075.39  4626.7 2074.52  4633.9 2071.67  4639.4 2072.19
  4656.7 2065.00  4699.4 2063.15  4873.1 2062.15  4895.9 2062.74  4912.3 2065.19
  4936.0 2062.72  4941.5 2056.70  4964.3 2055.42  4967.2 2054.06  4968.2 2053.56
  5018.2 2054.06  5023.8 2058.80  5136.4 2058.12  5256.0 2056.97  5837.2 2057.38
  5937.3 2055.97  6051.7 2057.20  6670.5 2059.10  6803.5 2063.47  6923.5 2067.00
  6982.4 2067.43  6989.9 2065.53  7031.9 2066.37  7135.8 2069.92  7248.7 2069.89
#Mann=9,-1,0
  4585.4   0.035       0  4699.4    0.07       0  4912.3    0.16       0
  4967.2    0.07       0  5018.2    0.16       0  5136.4   0.035       0
  6051.7    0.07       0  6803.5   0.035       0  7031.9   0.094       0
Bank Sta=4967.2,5018.2
Exp/Cntr=0.3,0.1

Type RM Length L Ch R = 1,25500,2000,2000,2000
BEGIN DESCRIPTION:
Sweetwater Creek Trib 27 51.0
END DESCRIPTION:
XS GIS Cut Line= 3
      1385204.96      6871437.99      1384805.30      6871316.22
      1382740.62      6870138.83
#Sta/Elev= 30
  4582.2 2090.37  4625.0 2084.91  4636.6 2082.23  4731.5 2074.21  4749.4 2072.70
  4759.9 2074.12  4838.9 2065.76  4873.5 2060.24  4980.7 2057.88  4980.8 2053.66
  4981.8 2053.16  5031.8 2053.66  5049.5 2054.46  5065.4 2059.06  5107.6 2058.44
  5748.1 2055.43  6282.8 2057.85  6349.7 2059.24  6407.8 2061.10  6501.5 2063.89
  6623.3 2063.88  6701.1 2063.62  6904.7 2063.48  7067.7 2064.42  7145.9 2064.38
  7179.9 2064.92  7227.5 2066.04  7243.3 2068.36  7353.6 2070.75  7376.8 2070.69
#Mann=17,-1,0
  4582.2    0.07       0  4625.0   0.035       0  4731.5    0.07       0
  4873.5    0.16       0  4980.8    0.07       0  5031.8    0.16       0
  5107.6   0.035       0  6282.8    0.07       0  6349.7   0.035       0
  6407.8    0.07       0  6623.3   0.035       0  6701.1    0.07       0
  6904.7   0.035       0  7067.7   0.063       0  7145.9   0.035       0
  7179.9   0.063       0  7353.6   0.035       0
Bank Sta=4980.8,5031.8
Exp/Cntr=0.3,0.1

Type RM Length L Ch R = 1,23500,500,500,500
BEGIN DESCRIPTION:
Sweetwater Creek Trib 27 47.0
END DESCRIPTION:
XS GIS Cut Line= 3
      1385455.01      6871388.01      1384146.00      6869946.99
      1384055.00      6868937.99
#Sta/Elev= 30
  3053.2 2101.10  3056.5 2101.10  3152.2 2095.86  3214.6 2085.21  3224.6 2084.53
  3435.3 2068.34  3647.6 2059.77  3860.4 2057.88  3888.8 2054.24  3923.9 2059.86
  3944.9 2057.15  4258.0 2055.30  4341.1 2055.26  4393.7 2055.18  4483.8 2055.21
  4529.3 2055.11  4626.5 2054.97  4922.0 2055.24  4957.8 2054.58  4960.0 2052.45
  4961.0 2051.95  5011.0 2052.45  5065.5 2052.65  5088.0 2060.08  5149.6 2060.83
  5219.9 2053.81  5348.7 2054.27  5470.9 2055.71  5671.7 2058.90  6013.1 2074.75
#Mann=15,-1,0
  3053.2    0.07       0  3056.5   0.035       0  3214.6    0.07       0
  3224.6   0.035       0  4258.0    0.16       0  4341.1   0.035       0
  4393.7    0.16       0  4483.8   0.035       0  4529.3    0.16       0
  4626.5   0.035       0  4960.0   0.035       0  5011.0   0.035       0
  5088.0    0.16       0  5348.7   0.033       0  5470.9   0.035       0
Bank Sta=4960,5011
Exp/Cntr=0.3,0.1

Type RM Length L Ch R = 1,23000,500,500,500
BEGIN DESCRIPTION:
Sweetwater Creek Trib 27 46.0
END DESCRIPTION:
XS GIS Cut Line= 3
      1385954.97      6870787.98      1384525.13      6869638.65
      1384105.02      6868788.04
#Sta/Elev= 30
  3165.5 2098.83  3264.1 2092.72  3614.2 2071.52  3663.8 2071.69  3791.8 2060.83
  3827.0 2058.90  3847.9 2060.45  3884.0 2055.97  3901.1 2055.57  3936.5 2054.66
  4270.4 2053.95  4397.1 2053.56  4630.5 2053.15  4631.8 2052.35  4687.5 2053.15
  4788.6 2053.62  4923.0 2054.60  5003.2 2053.18  5121.2 2055.25  5363.8 2055.76
  5412.9 2058.28  5463.4 2057.62  5755.2 2073.07  5828.1 2074.80  5845.0 2077.61
  5904.1 2080.14  5912.3 2083.74  5917.9 2081.40  5926.4 2080.78  5948.7 2084.05
#Mann=10,-1,0
  3165.5    0.07       0  3264.1   0.035       0  3901.1    0.16       0
  3936.5   0.033       0  4270.4   0.035       0  4397.1    0.07       0
  4630.5   0.033       0  4687.5    0.07       0  4788.6   0.033       0
  5363.8   0.035       0
Bank Sta=4630.5,4687.5
Exp/Cntr=0.3,0.1

Type RM Length L Ch R = 1,22500,500,500,500
BEGIN DESCRIPTION:
Sweetwater Creek Trib 27 45.0
END DESCRIPTION:
XS GIS Cut Line= 3
      1385854.98      6870587.98      1384924.87      6869617.80
      1384205.01      6868638.02
#Sta/Elev= 30
  3656.0 2084.57  3811.5 2076.90  3924.7 2069.56  4044.8 2064.85  4101.4 2060.75
  4156.9 2059.21  4172.2 2060.17  4188.1 2058.92  4193.6 2058.87  4214.7 2054.35
  4228.8 2053.77  4372.2 2053.95  4435.5 2052.69  4440.9 2052.03  4442.2 2051.23
  4496.6 2051.23  4497.9 2052.03  4526.0 2053.69  4554.3 2052.81  4625.1 2053.53
  4872.6 2052.45  5346.8 2053.43  5585.2 2054.87  5886.7 2072.51  5901.4 2072.01
  5966.2 2076.41  5980.1 2075.54  6001.7 2078.35  6037.2 2080.22  6215.8 2086.06
#Mann=9,-1,0
  3656.0   0.035       0  4156.9    0.16       0  4188.1   0.033       0
  4372.2   0.035       0  4435.5    0.07       0  4440.9    0.07       0
  4497.9    0.07       0  5346.8   0.033       0  5585.2   0.035       0
Bank Sta=4440.9,4497.9
Exp/Cntr=0.3,0.1

Type RM Length L Ch R = 1,22000,500,500,500
BEGIN DESCRIPTION:
Sweetwater Creek Trib 27 44.0
END DESCRIPTION:
XS GIS Cut Line= 3
      1385805.00      6870387.99      1385320.34      6869422.85
      1384304.99      6868587.99
#Sta/Elev= 30
  3920.0 2076.82  4084.7 2071.13  4218.7 2064.56  4224.3 2065.62  4241.0 2063.42
  4393.3 2058.04  4427.3 2058.38  4457.1 2059.79  4464.3 2057.37  4469.9 2058.60
  4486.7 2053.15  4737.6 2052.53  4804.9 2052.38  4809.0 2051.57  4810.4 2050.77
  4864.8 2050.77  4866.1 2051.57  5473.6 2052.29  5663.2 2053.11  5731.9 2053.77
  5762.9 2055.18  5887.6 2064.05  6044.0 2073.15  6058.4 2074.92  6072.7 2074.55
  6101.4 2077.33  6144.4 2078.87  6165.3 2080.97  6264.3 2084.90  6314.5 2085.38
#Mann=9,-1,0
  3920.0   0.035       0  4393.3    0.16       0  4427.3    0.07       0
  4737.6   0.033       0  4809.0   0.033       0  4866.1   0.033       0
  5473.6    0.07       0  5663.2   0.033       0  5762.9   0.035       0
Bank Sta=4809,4866.1
Exp/Cntr=0.3,0.1

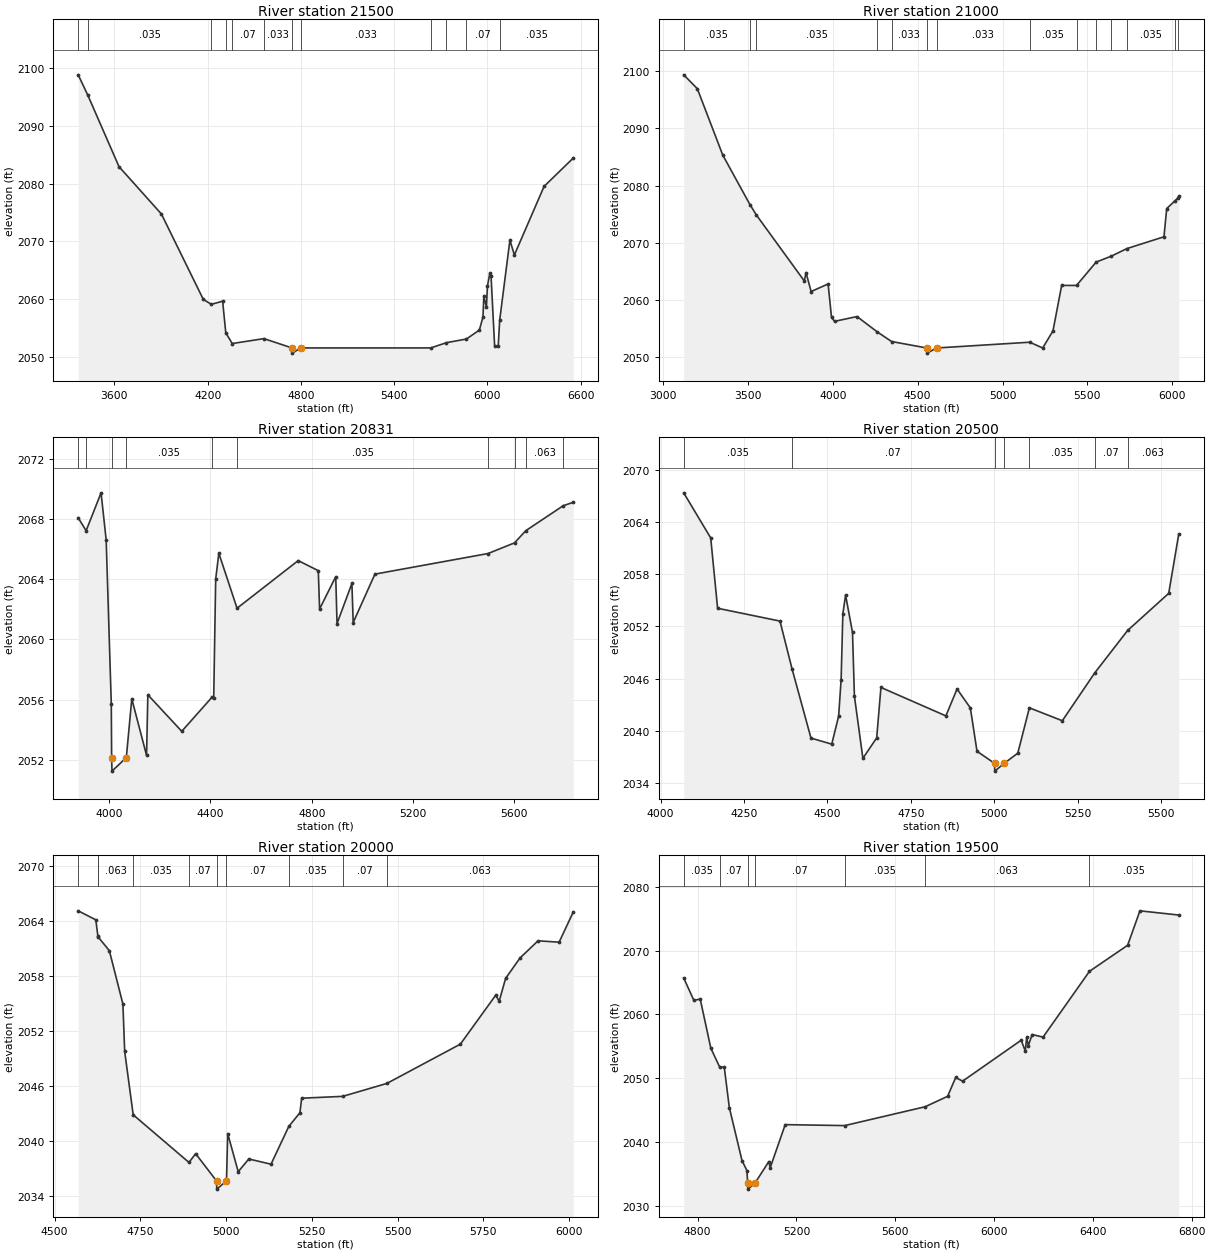
Type RM Length L Ch R = 1,21500,500,500,500
BEGIN DESCRIPTION:
Sweetwater Creek Trib 27 43.0
END DESCRIPTION:
XS GIS Cut Line= 3
      1385955.00      6870788.02      1385722.29      6869171.59
      1384304.96      6868537.98
#Sta/Elev= 30
  3366.9 2098.83  3427.4 2095.40  3629.6 2082.94  3902.4 2074.75  4172.0 2059.97
  4223.8 2059.11  4296.4 2059.66  4316.7 2054.19  4358.2 2052.33  4562.1 2053.18
  4742.3 2051.57  4743.7 2050.67  4800.3 2051.57  5635.9 2051.57  5736.6 2052.48
  5865.1 2053.11  5948.3 2054.66  5971.5 2056.92  5977.0 2060.49  5993.8 2058.64
  6000.2 2062.25  6015.7 2064.53  6023.4 2064.10  6046.6 2051.87  6069.8 2051.94
  6079.2 2056.40  6144.9 2070.22  6173.6 2067.65  6364.7 2079.52  6552.5 2084.43
#Mann=12,-1,0
  3366.9    0.07       0  3427.4   0.035       0  4223.8    0.07       0
  4316.7   0.035       0  4358.2    0.07       0  4562.1   0.033       0
  4742.3   0.033       0  4800.3   0.033       0  5635.9    0.07       0
  5736.6   0.033       0  5865.1    0.07       0  6079.2   0.035       0
Bank Sta=4742.3,4800.3
Exp/Cntr=0.3,0.1

Type RM Length L Ch R = 1,21000,169,169,169
BEGIN DESCRIPTION:
Sweetwater Creek Trib 27 42.0
END DESCRIPTION:
XS GIS Cut Line= 3
      1386005.00      6870788.05      1386078.78      6868911.10
      1386255.01      6867887.97
#Sta/Elev= 30
  3121.6 2099.37  3201.7 2096.95  3351.8 2085.32  3512.1 2076.65  3549.6 2074.85
  3832.2 2063.29  3842.2 2064.76  3872.2 2061.45  3972.3 2062.77  3992.3 2056.95
  4010.0 2056.23  4142.4 2057.07  4262.8 2054.37  4346.2 2052.70  4553.8 2051.57
  4555.1 2050.67  4611.8 2051.57  5160.1 2052.58  5236.5 2051.57  5297.1 2054.57
  5348.2 2062.52  5435.6 2062.51  5551.3 2066.60  5641.5 2067.65  5732.2 2068.96
  5950.9 2071.03  5967.1 2075.97  6017.3 2077.36  6031.9 2077.81  6038.2 2078.09
#Mann=14,-1,0
  3121.6   0.035       0  3512.1    0.07       0  3549.6   0.035       0
  4262.8    0.07       0  4346.2   0.033       0  4553.8   0.033       0
  4611.8   0.033       0  5160.1   0.035       0  5435.6   0.063       0
  5551.3   0.035       0  5641.5   0.063       0  5732.2   0.035       0
  6017.3   0.063       0  6031.9   0.094       0
Bank Sta=4553.8,4611.8
Exp/Cntr=0.3,0.1

Type RM Length L Ch R = 1,20831,331,331,331
BEGIN DESCRIPTION:
Sweetwater Creek Trib 27 41.1
END DESCRIPTION:
XS GIS Cut Line= 5
      1386379.97      6870087.38      1386268.87      6869337.42
      1386214.53      6868977.44      1386185.53      6868531.87
      1386251.25      6868151.42
#Sta/Elev= 30
  3877.8 2068.10  3909.2 2067.24  3968.2 2069.76  3988.4 2066.62  4008.6 2055.70
  4009.9 2052.14  4011.3 2051.24  4067.9 2052.14  4089.5 2056.05  4147.8 2052.29
  4152.9 2056.32  4286.8 2053.89  4407.9 2056.19  4413.0 2056.13  4420.8 2064.02
  4433.2 2065.74  4505.1 2062.08  4746.6 2065.25  4825.9 2064.58  4831.0 2062.03
  4894.8 2064.18  4899.9 2061.06  4958.6 2063.73  4963.7 2061.13  5049.5 2064.35
  5496.1 2065.72  5600.7 2066.43  5645.1 2067.24  5792.8 2068.90  5832.6 2069.13
#Mann=10,-1,0
  3877.8    0.07       0  3909.2   0.035       0  4009.9   0.035       0
  4067.9   0.035       0  4407.9    0.07       0  4505.1   0.035       0
  5496.1   0.063       0  5600.7   0.035       0  5645.1   0.063       0
  5792.8   0.035       0
Bank Sta=4009.9,4067.9
Exp/Cntr=0.3,0.1

Type RM Length L Ch R = 1,20500,500,500,500
BEGIN DESCRIPTION:
Sweetwater Creek Trib 27 41.0
END DESCRIPTION:
XS GIS Cut Line= 3
      1386744.56      6869886.01      1386499.92      6868987.93
      1386555.00      6868437.98
#Sta/Elev= 30
  4069.2 2067.41  4150.1 2062.21  4170.8 2054.10  4357.7 2052.62  4393.7 2047.13
  4450.6 2039.13  4512.8 2038.43  4533.5 2041.67  4540.9 2045.88  4546.1 2053.47
  4554.3 2055.62  4575.0 2051.31  4580.7 2043.97  4606.1 2036.80  4647.5 2039.15
  4660.2 2044.97  4854.8 2041.69  4888.3 2044.79  4928.1 2042.61  4948.1 2037.61
  5000.6 2036.22  5001.2 2035.32  5029.6 2036.22  5070.3 2037.39  5105.0 2042.62
  5203.7 2041.13  5301.3 2046.67  5399.4 2051.54  5522.5 2055.82  5552.7 2062.67
#Mann=7,-1,0
  4069.2   0.035       0  4393.7    0.07       0  5000.6    0.07       0
  5029.6    0.07       0  5105.0   0.035       0  5301.3    0.07       0
  5399.4   0.063       0
Bank Sta=5000.6,5029.6
Exp/Cntr=0.3,0.1

Type RM Length L Ch R = 1,20000,500,500,500
BEGIN DESCRIPTION:
Sweetwater Creek Trib 27 40.0
END DESCRIPTION:
XS GIS Cut Line= 3
      1387004.99      6869637.97      1386890.00      6869222.60
      1386654.99      6868237.95
#Sta/Elev= 30
  4569.0 2065.10  4620.4 2064.12  4626.6 2062.30  4627.0 2062.26  4659.9 2060.75
  4699.4 2054.94  4704.6 2049.76  4729.4 2042.85  4892.1 2037.65  4911.4 2038.61
  4972.3 2035.64  4973.0 2034.74  5001.4 2035.64  5004.9 2040.80  5035.6 2036.64
  5066.4 2038.03  5131.2 2037.46  5183.0 2041.58  5215.4 2043.07  5220.6 2044.66
  5340.1 2044.86  5468.9 2046.27  5683.3 2050.56  5786.1 2055.89  5796.4 2055.25
  5815.1 2057.73  5857.2 2059.96  5909.6 2061.83  5971.1 2061.68  6012.3 2064.97
#Mann=10,-1,0
  4569.0   0.063       0  4626.6   0.035       0  4627.0   0.063       0
  4729.4   0.035       0  4892.1    0.07       0  4972.3    0.07       0
  5001.4    0.07       0  5183.0   0.035       0  5340.1    0.07       0
  5468.9   0.063       0
Bank Sta=4972.3,5001.4
Exp/Cntr=0.3,0.1

Type RM Length L Ch R = 1,19500,500,500,500
BEGIN DESCRIPTION:
Sweetwater Creek Trib 27 39.0
END DESCRIPTION:
XS GIS Cut Line= 3
      1387254.99      6869688.03      1387312.39      6869438.34
      1386504.99      6867887.98
#Sta/Elev= 30
  4743.8 2065.70  4784.9 2062.21  4810.7 2062.40  4853.5 2054.73  4889.8 2051.73
  4908.0 2051.75  4928.5 2045.43  4979.8 2037.14  5000.0 2035.55  5002.6 2033.57
  5003.3 2032.67  5031.7 2033.57  5088.4 2036.98  5094.0 2036.02  5154.7 2042.76
  5395.6 2042.61  5721.4 2045.56  5812.2 2047.19  5844.9 2050.14  5872.7 2049.56
  6110.1 2055.97  6126.6 2054.26  6132.2 2056.41  6139.1 2055.12  6154.3 2056.86
  6198.5 2056.45  6386.5 2066.75  6540.9 2070.82  6590.7 2076.21  6748.0 2075.55
#Mann=7,-1,0
  4743.8   0.035       0  4889.8    0.07       0  5002.6    0.07       0
  5031.7    0.07       0  5395.6   0.035       0  5721.4   0.063       0
  6386.5   0.035       0
Bank Sta=5002.6,5031.7
Exp/Cntr=0.3,0.1

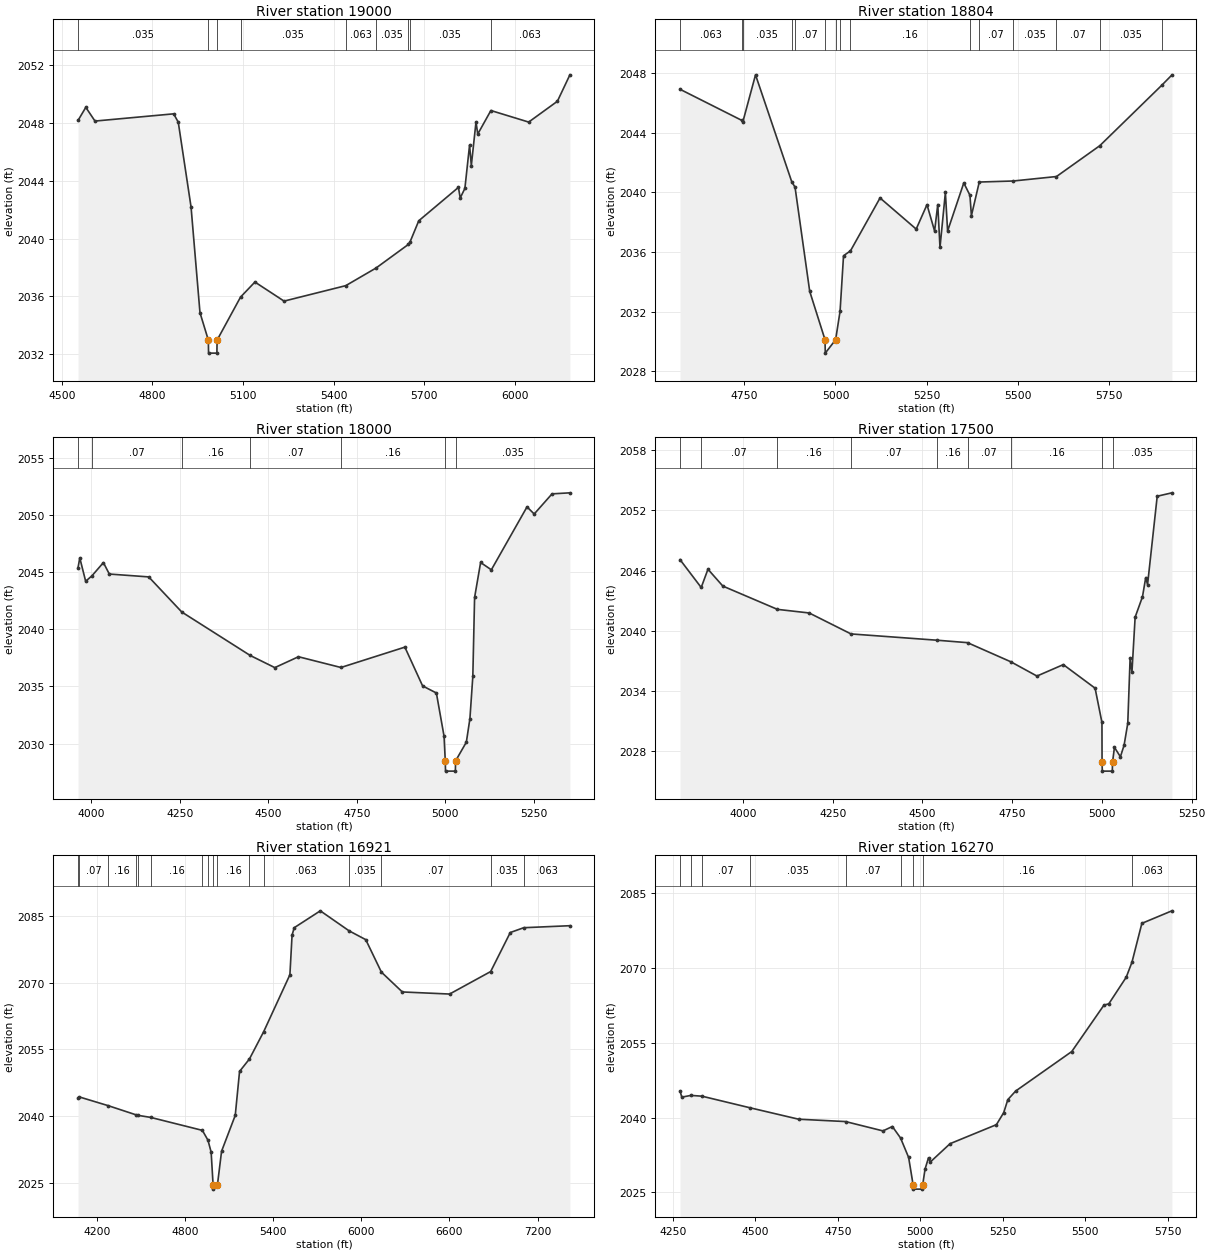
Type RM Length L Ch R = 1,19000,196,196,196
BEGIN DESCRIPTION:
Sweetwater Creek Trib 27 38.0
END DESCRIPTION:
XS GIS Cut Line= 4
      1388011.37      6869698.60      1387771.35      6869322.22
      1387128.56      6868954.67      1386899.32      6868576.24
#Sta/Elev= 30
  4553.6 2048.17  4579.4 2049.08  4609.8 2048.13  4870.5 2048.63  4885.7 2048.05
  4928.0 2042.19  4957.6 2034.87  4985.3 2032.97  4986.0 2032.07  5013.6 2032.07
  5014.3 2032.97  5092.0 2035.95  5139.6 2036.99  5236.1 2035.67  5440.5 2036.74
  5540.8 2037.96  5647.7 2039.59  5653.1 2039.75  5682.3 2041.23  5813.7 2043.54
  5819.6 2042.81  5835.1 2043.47  5850.6 2046.47  5856.4 2045.05  5871.9 2048.07
  5877.7 2047.23  5921.2 2048.86  6046.4 2048.06  6141.5 2049.50  6182.9 2051.33
#Mann=9,-1,0
  4553.6   0.035       0  4985.3   0.035       0  5014.3   0.035       0
  5092.0   0.035       0  5440.5   0.063       0  5540.8   0.035       0
  5647.7   0.063       0  5653.1   0.035       0  5921.2   0.063       0
Bank Sta=4985.3,5014.3
Exp/Cntr=0.3,0.1

Type RM Length L Ch R = 1,18804,804,804,804
BEGIN DESCRIPTION:
Sweetwater Creek Trib 27 37.0
END DESCRIPTION:
XS GIS Cut Line= 3
      1388111.21      6869434.90      1387805.02      6869138.00
      1387050.78      6868605.45
#Sta/Elev= 30
  4573.5 2046.93  4742.3 2044.85  4746.0 2044.75  4780.7 2047.90  4880.2 2040.71
  4889.1 2040.36  4929.4 2033.36  4971.4 2030.11  4972.1 2029.21  5000.5 2030.11
  5012.7 2032.02  5022.2 2035.75  5041.3 2036.08  5122.4 2039.63  5221.6 2037.54
  5251.2 2039.18  5272.1 2037.41  5280.8 2039.19  5286.9 2036.31  5301.7 2040.00
  5307.8 2037.41  5352.2 2040.64  5369.1 2039.81  5373.1 2038.44  5394.7 2040.70
  5487.8 2040.77  5606.6 2041.07  5725.4 2043.14  5895.1 2047.19  5923.3 2047.89
#Mann=15,-1,0
  4573.5   0.063       0  4742.3    0.07       0  4746.0   0.035       0
  4880.2   0.063       0  4889.1    0.07       0  4971.4    0.07       0
  5000.5    0.07       0  5012.7   0.035       0  5041.3    0.16       0
  5369.1   0.035       0  5394.7    0.07       0  5487.8   0.035       0
  5606.6    0.07       0  5725.4   0.035       0  5895.1   0.063       0
Bank Sta=4971.4,5000.5
Exp/Cntr=0.3,0.1

Type RM Length L Ch R = 1,18000,500,500,500
BEGIN DESCRIPTION:
Sweetwater Creek Trib 27 36.0
END DESCRIPTION:
XS GIS Cut Line= 3
      1388120.17      6869411.51      1387650.45      6868486.99
      1387605.00      6868138.04
#Sta/Elev= 30
  3963.0 2045.37  3968.0 2046.24  3984.6 2044.20  4002.2 2044.67  4034.7 2045.83
  4051.4 2044.83  4162.6 2044.58  4256.0 2041.51  4449.3 2037.71  4518.7 2036.65
  4585.5 2037.60  4705.4 2036.66  4885.9 2038.44  4936.0 2035.05  4974.9 2034.43
  4996.6 2030.65  5000.0 2028.50  5000.7 2027.60  5028.5 2027.60  5029.2 2028.50
  5059.5 2030.13  5069.6 2032.19  5077.8 2035.88  5082.8 2042.78  5099.8 2045.84
  5130.1 2045.20  5230.8 2050.70  5251.1 2050.08  5301.5 2051.84  5351.9 2051.93
#Mann=7,-1,0
  3963.0   0.063       0  4002.2    0.07       0  4256.0    0.16       0
  4449.3    0.07       0  4705.4    0.16       0  5000.0    0.07       0
  5029.2   0.035       0
Bank Sta=5000,5029.2
Exp/Cntr=0.3,0.1

Type RM Length L Ch R = 1,17500,579,579,579
BEGIN DESCRIPTION:
Sweetwater Creek Trib 27 35.0
END DESCRIPTION:
XS GIS Cut Line= 3
      1388133.38      6869445.30      1387997.30      6868278.20
      1387955.01      6868088.05
#Sta/Elev= 30
  3825.0 2047.10  3884.0 2044.32  3902.8 2046.14  3944.3 2044.46  4096.2 2042.14
  4184.7 2041.78  4301.2 2039.69  4542.0 2039.06  4625.6 2038.82  4746.4 2036.91
  4819.0 2035.49  4892.4 2036.63  4980.9 2034.28  5000.0 2030.86  5000.3 2026.91
  5001.0 2026.01  5028.8 2026.01  5029.5 2026.91  5034.8 2028.38  5051.4 2027.44
  5061.7 2028.60  5071.9 2030.78  5078.4 2037.25  5083.5 2035.86  5092.4 2041.36
  5112.9 2043.40  5121.9 2045.31  5127.0 2044.61  5153.9 2053.42  5194.8 2053.76
#Mann=9,-1,0
  3825.0   0.063       0  3884.0    0.07       0  4096.2    0.16       0
  4301.2    0.07       0  4542.0    0.16       0  4625.6    0.07       0
  4746.4    0.16       0  5000.3    0.07       0  5029.5   0.035       0
Bank Sta=5000.3,5029.5
Exp/Cntr=0.3,0.1

Type RM Length L Ch R = 1,16921,651,651,651
BEGIN DESCRIPTION:
Sweetwater Creek Trib 27 34.0
END DESCRIPTION:
XS GIS Cut Line= 4
      1388139.74      6869398.10      1388486.56      6868536.42
      1389378.03      6867326.06      1388804.99      6868038.01
#Sta/Elev= 30
  4073.0 2044.09  4081.3 2044.32  4278.8 2042.35  4470.3 2040.27  4483.2 2040.17
  4567.4 2039.72  4918.9 2036.81  4957.0 2034.60  4978.6 2031.93  4992.0 2024.52
  4992.7 2023.62  5021.2 2024.52  5049.6 2032.13  5142.6 2040.18  5171.9 2050.04
  5239.2 2052.84  5336.3 2058.98  5514.4 2071.74  5529.1 2080.64  5543.7 2082.30
  5721.2 2086.09  5916.9 2081.60  6030.4 2079.62  6136.8 2072.33  6279.1 2067.88
  6600.7 2067.41  6880.1 2072.46  7013.5 2081.22  7105.0 2082.30  7419.0 2082.75
#Mann=16,-1,0
  4073.0   0.063       0  4081.3    0.07       0  4278.8    0.16       0
  4470.3    0.07       0  4483.2   0.035       0  4567.4    0.16       0
  4918.9    0.07       0  4957.0    0.16       0  4992.0    0.07       0
  5021.2    0.16       0  5239.2    0.07       0  5336.3   0.063       0
  5916.9   0.035       0  6136.8    0.07       0  6880.1   0.035       0
  7105.0   0.063       0
Bank Sta=4992,5021.2
Exp/Cntr=0.3,0.1

Type RM Length L Ch R = 1,16270,270,270,270
BEGIN DESCRIPTION:
Sweetwater Creek Trib 27 33.0
END DESCRIPTION:
XS GIS Cut Line= 3
      1388255.43      6869466.17      1388808.32      6868991.34
      1389104.98      6868288.04
#Sta/Elev= 30
  4271.2 2045.33  4276.6 2044.09  4304.4 2044.44  4337.9 2044.28  4483.5 2041.96
  4631.1 2039.67  4773.3 2039.20  4886.8 2037.33  4915.3 2038.21  4940.1 2035.92
  4964.7 2032.01  4978.2 2026.57  4978.9 2025.67  5006.7 2025.67  5007.4 2026.57
  5014.5 2029.69  5025.0 2031.95  5030.4 2031.10  5090.4 2034.77  5231.0 2038.58
  5253.2 2041.00  5265.6 2043.59  5289.3 2045.31  5459.5 2053.22  5557.1 2062.51
  5571.9 2062.78  5624.8 2068.11  5642.2 2071.12  5672.2 2078.89  5763.3 2081.40
#Mann=9,-1,0
  4271.2   0.063       0  4304.4   0.035       0  4337.9    0.07       0
  4483.5   0.035       0  4773.3    0.07       0  4940.1    0.16       0
  4978.2    0.07       0  5007.4    0.16       0  5642.2   0.063       0
Bank Sta=4978.2,5007.4
Exp/Cntr=0.3,0.1

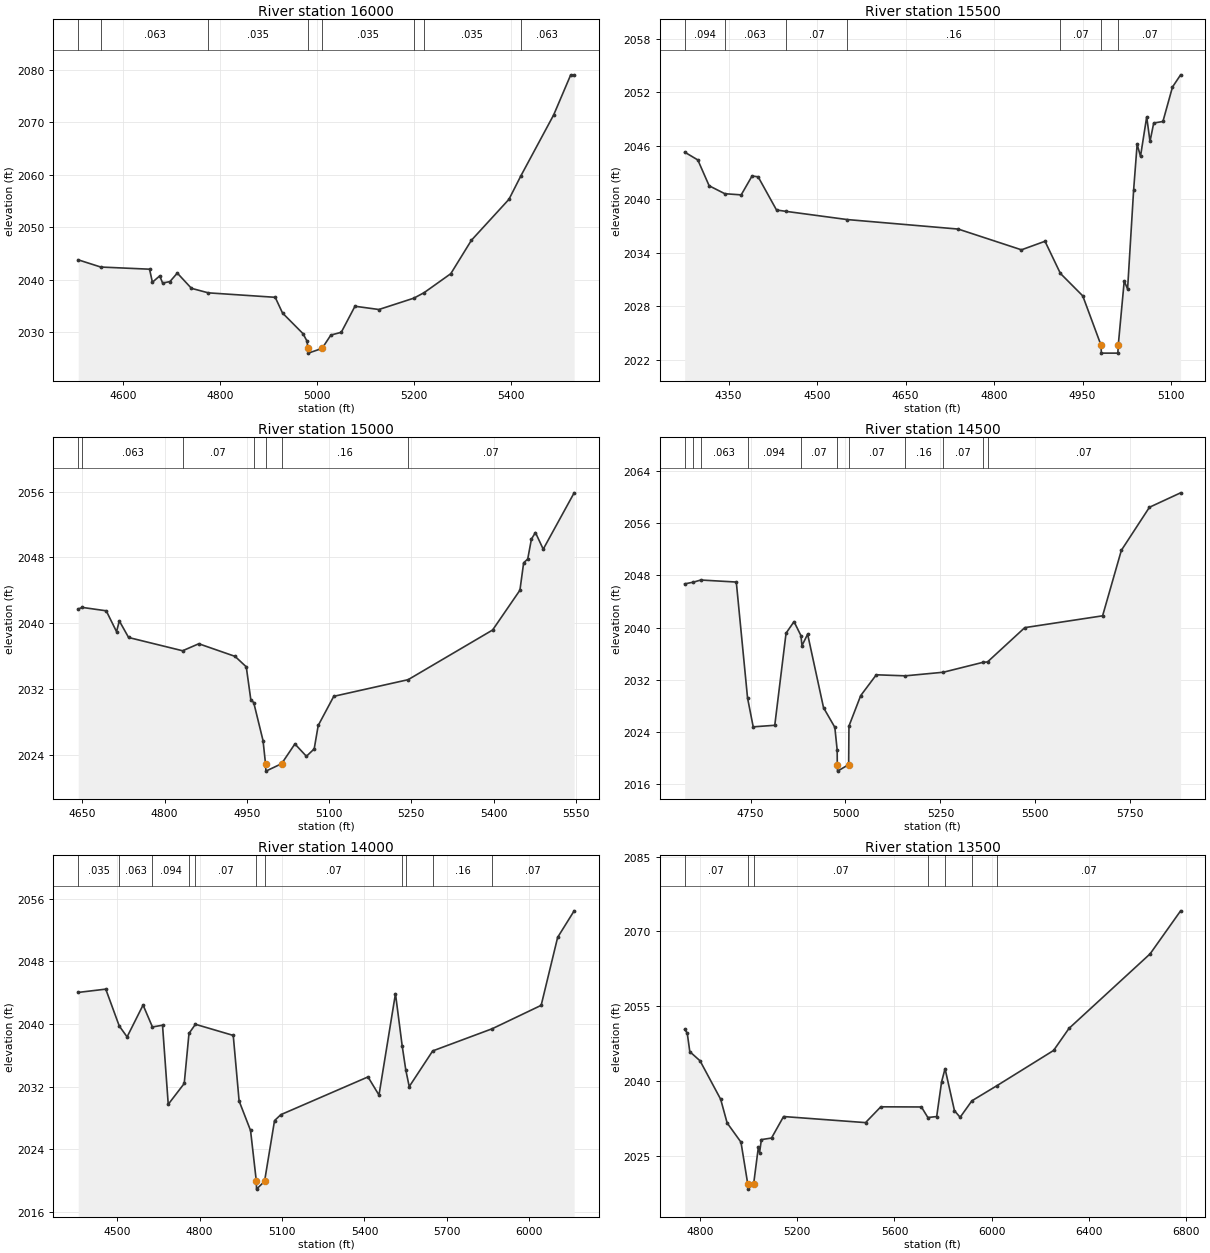
Type RM Length L Ch R = 1,16000,500,500,500
BEGIN DESCRIPTION:
Sweetwater Creek Trib 27 32.0
END DESCRIPTION:
XS GIS Cut Line= 3
      1388747.99      6869563.88      1389016.93      6869151.05
      1389404.99      6868788.01
#Sta/Elev= 30
  4507.3 2043.82  4553.8 2042.45  4654.6 2042.04  4660.5 2039.56  4675.6 2040.76
  4681.6 2039.41  4696.7 2039.68  4711.9 2041.30  4741.1 2038.40  4775.9 2037.54
  4914.1 2036.69  4929.2 2033.70  4971.4 2029.78  4979.8 2028.35  4981.6 2026.97
  4982.4 2026.07  5010.9 2026.97  5029.0 2029.51  5050.5 2030.03  5078.8 2034.99
  5128.2 2034.37  5200.4 2036.53  5221.5 2037.57  5276.7 2041.19  5319.2 2047.54
  5396.8 2055.34  5421.0 2059.73  5489.2 2071.41  5524.3 2079.01  5531.4 2079.02
#Mann=8,-1,0
  4507.3   0.094       0  4553.8   0.063       0  4775.9   0.035       0
  4981.6   0.035       0  5010.9   0.035       0  5200.4   0.063       0
  5221.5   0.035       0  5421.0   0.063       0
Bank Sta=4981.6,5010.9
Exp/Cntr=0.3,0.1

Type RM Length L Ch R = 1,15500,500,500,500
BEGIN DESCRIPTION:
Sweetwater Creek Trib 27 31.0
END DESCRIPTION:
XS GIS Cut Line= 3
      1388705.03      6869637.99      1389402.81      6869443.44
      1389505.04      6869387.98
#Sta/Elev= 30
  4275.6 2045.29  4297.9 2044.41  4317.1 2041.51  4343.7 2040.62  4371.4 2040.49
  4389.8 2042.61  4400.1 2042.52  4431.3 2038.79  4447.3 2038.64  4550.9 2037.72
  4739.3 2036.65  4846.5 2034.32  4886.4 2035.28  4912.5 2031.67  4950.4 2029.15
  4981.3 2023.62  4982.0 2022.72  5009.9 2022.72  5010.6 2023.62  5020.7 2030.82
  5026.4 2029.92  5036.6 2041.00  5042.6 2046.18  5048.3 2044.82  5058.8 2049.25
  5064.4 2046.49  5070.7 2048.56  5086.3 2048.73  5102.5 2052.60  5116.3 2053.97
#Mann=7,-1,0
  4275.6   0.094       0  4343.7   0.063       0  4447.3    0.07       0
  4550.9    0.16       0  4912.5    0.07       0  4981.3    0.07       0
  5010.6    0.07       0
Bank Sta=4981.3,5010.6
Exp/Cntr=0.3,0.1

Type RM Length L Ch R = 1,15000,500,500,500
BEGIN DESCRIPTION:
Sweetwater Creek Trib 27 30.0
END DESCRIPTION:
XS GIS Cut Line= 3
      1388955.00      6869838.00      1389304.95      6869911.08
      1389704.98      6869538.02
#Sta/Elev= 30
  4642.5 2041.74  4650.0 2041.93  4693.6 2041.52  4712.4 2038.99  4717.5 2040.29
  4734.4 2038.28  4832.9 2036.67  4862.4 2037.52  4928.5 2035.99  4949.0 2034.72
  4957.3 2030.73  4962.6 2030.38  4979.6 2025.76  4984.1 2022.96  4984.8 2022.06
  5013.4 2022.96  5037.7 2025.36  5058.7 2023.86  5072.9 2024.76  5080.2 2027.60
  5108.6 2031.14  5244.2 2033.16  5398.3 2039.19  5448.1 2044.02  5454.9 2047.35
  5462.3 2047.80  5469.1 2050.23  5476.4 2051.02  5490.6 2049.00  5547.0 2055.84
#Mann=7,-1,0
  4642.5   0.094       0  4650.0   0.063       0  4832.9    0.07       0
  4962.6    0.16       0  4984.1    0.07       0  5013.4    0.16       0
  5244.2    0.07       0
Bank Sta=4984.1,5013.4
Exp/Cntr=0.3,0.1

Type RM Length L Ch R = 1,14500,500,500,500
BEGIN DESCRIPTION:
Sweetwater Creek Trib 27 29.0
END DESCRIPTION:
XS GIS Cut Line= 3
      1389204.96      6870538.03      1389552.94      6870297.00
      1389754.99      6869438.04
#Sta/Elev= 30
  4576.7 2046.69  4599.3 2046.95  4619.3 2047.28  4712.6 2046.97  4742.2 2029.23
  4757.1 2024.80  4813.9 2025.04  4843.6 2039.14  4864.6 2040.91  4882.8 2038.76
  4885.5 2037.23  4900.4 2038.99  4942.3 2027.73  4972.0 2024.73  4978.2 2021.25
  4978.5 2019.02  4979.2 2018.02  5008.4 2019.02  5009.2 2024.92  5040.1 2029.58
  5081.2 2032.77  5157.6 2032.61  5257.5 2033.16  5361.5 2034.67  5374.0 2034.74
  5472.1 2039.99  5677.0 2041.80  5726.4 2051.83  5800.3 2058.42  5882.4 2060.63
#Mann=11,-1,0
  4576.7   0.035       0  4599.3   0.094       0  4619.3   0.063       0
  4742.2   0.094       0  4882.8    0.07       0  4978.5    0.07       0
  5008.4    0.07       0  5157.6    0.16       0  5257.5    0.07       0
  5361.5    0.16       0  5374.0    0.07       0
Bank Sta=4978.5,5008.4
Exp/Cntr=0.3,0.1

Type RM Length L Ch R = 1,14000,500,500,500
BEGIN DESCRIPTION:
Sweetwater Creek Trib 27 28.0
END DESCRIPTION:
XS GIS Cut Line= 3
      1389305.02      6871087.99      1389816.94      6870700.55
      1389855.00      6869537.98
#Sta/Elev= 30
  4358.0 2044.05  4458.3 2044.47  4507.3 2039.77  4535.9 2038.37  4594.1 2042.44
  4628.1 2039.64  4664.9 2039.86  4685.7 2029.76  4743.9 2032.42  4761.2 2038.81
  4784.6 2039.98  4922.3 2038.56  4943.7 2030.18  4985.3 2026.42  5006.4 2019.93
  5007.1 2018.93  5036.3 2019.93  5072.6 2027.68  5095.6 2028.44  5412.8 2033.26
  5452.8 2030.94  5512.8 2043.89  5537.3 2037.21  5550.4 2034.14  5562.9 2032.02
  5648.3 2036.58  5864.8 2039.41  6043.1 2042.40  6103.1 2051.08  6163.2 2054.47
#Mann=11,-1,0
  4358.0   0.035       0  4507.3   0.063       0  4628.1   0.094       0
  4761.2   0.063       0  4784.6    0.07       0  5006.4    0.07       0
  5036.3    0.07       0  5537.3    0.16       0  5550.4    0.07       0
  5648.3    0.16       0  5864.8    0.07       0
Bank Sta=5006.4,5036.3
Exp/Cntr=0.3,0.1

Type RM Length L Ch R = 1,13500,500,500,500
BEGIN DESCRIPTION:
Sweetwater Creek Trib 27 27.0
END DESCRIPTION:
XS GIS Cut Line= 3
      1390354.99      6871087.98      1390272.53      6870838.03
      1389754.99      6869137.96
#Sta/Elev= 30
  4736.8 2050.34  4747.3 2049.62  4757.9 2045.88  4800.0 2044.05  4884.9 2036.33
  4911.4 2031.59  4968.4 2027.73  4996.4 2019.31  4997.0 2018.31  5020.4 2019.31
  5039.8 2026.67  5045.0 2025.63  5052.3 2028.24  5094.1 2028.56  5143.6 2032.87
  5480.9 2031.65  5543.6 2034.82  5710.8 2034.79  5737.3 2032.67  5773.6 2032.87
  5793.8 2039.84  5808.0 2042.47  5846.7 2034.04  5870.0 2032.72  5918.5 2036.03
  6021.7 2039.07  6254.4 2046.12  6317.9 2050.55  6651.6 2065.50  6777.1 2074.13
#Mann=7,-1,0
  4736.8    0.07       0  4996.4    0.07       0  5020.4    0.07       0
  5737.3    0.16       0  5808.0    0.07       0  5918.5   0.035       0
  6021.7    0.07       0
Bank Sta=4996.4,5020.4
Exp/Cntr=0.3,0.1