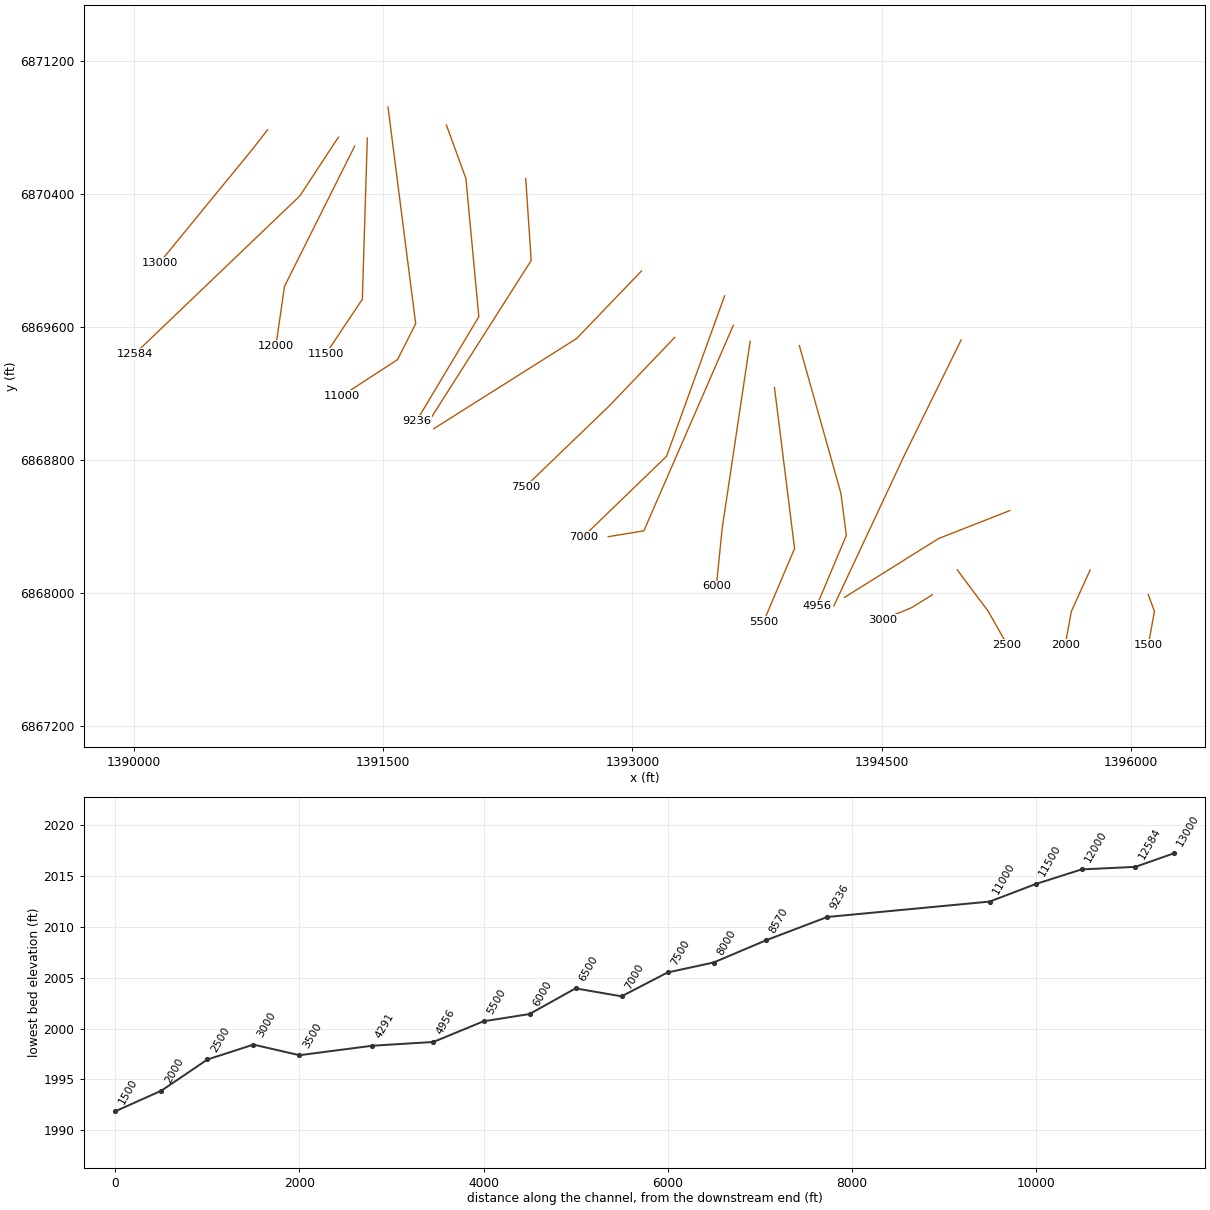
HEC-RAS study Sweetwater Creek Trib 27.prj: Sweetwater Creek Trib 27 Base Level Engineering

--- Sweetwater Creek Trib 27.g01 (geometry) --- (continued)

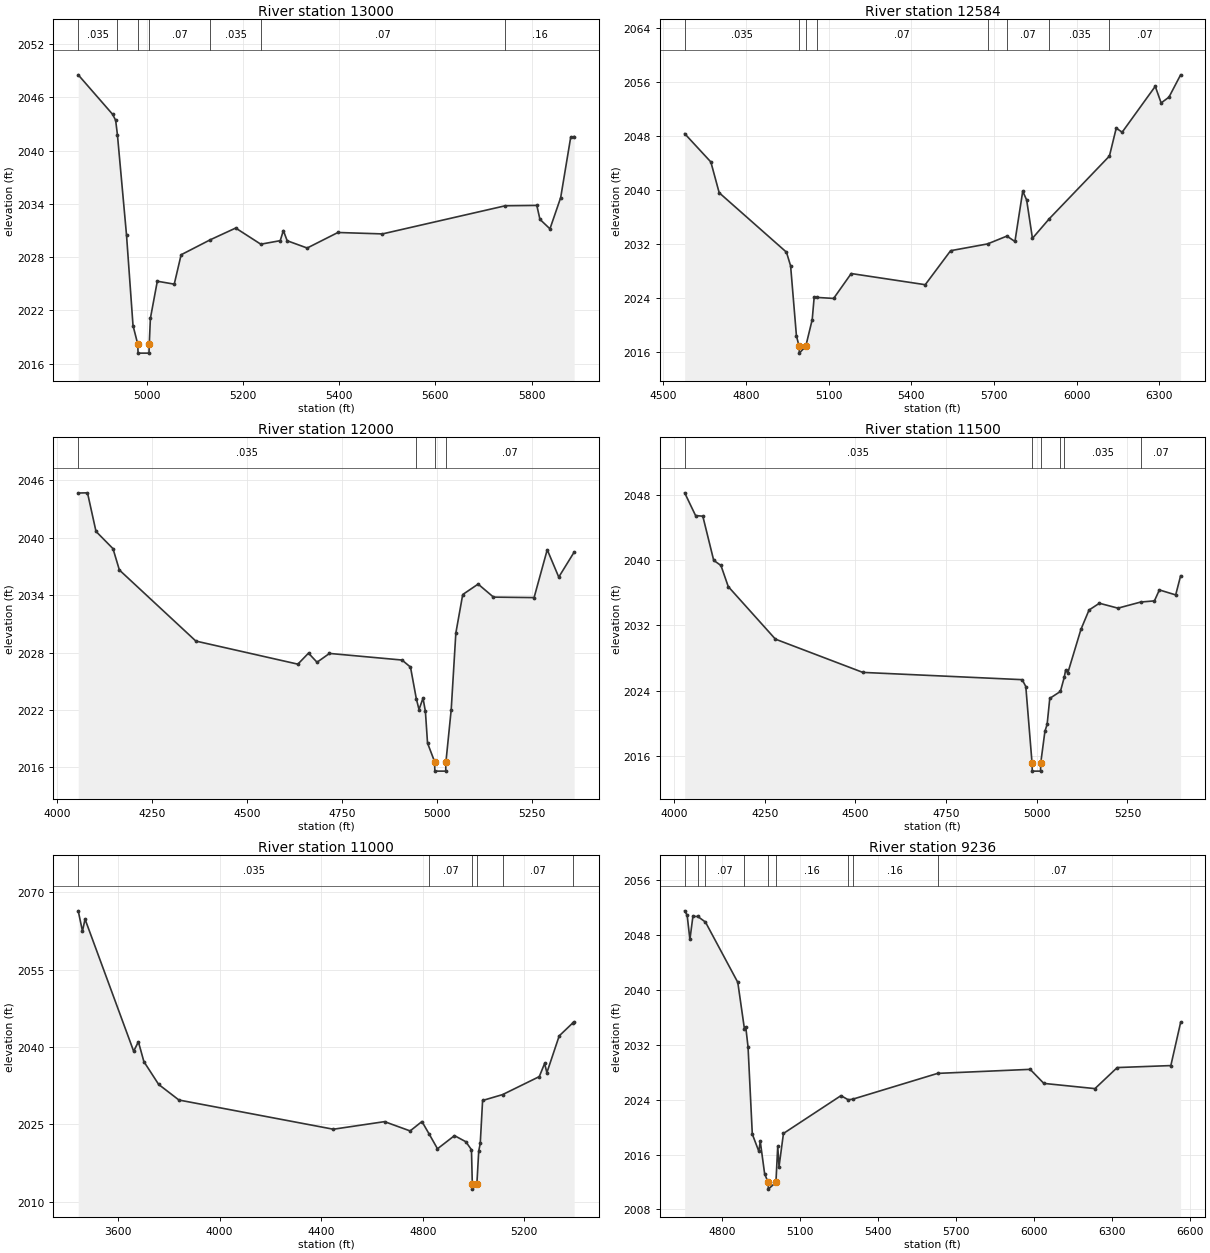
Type RM Length L Ch R = 1,13000,416,416,416
BEGIN DESCRIPTION:
Sweetwater Creek Trib 27 26.0
END DESCRIPTION:
XS GIS Cut Line= 3
      1390804.98      6870787.97      1390717.61      6870675.52
      1390154.98      6869987.98
#Sta/Elev= 30
  4857.6 2048.54  4929.1 2044.09  4935.4 2043.42  4939.1 2041.79  4958.0 2030.49
  4971.5 2020.30  4981.4 2018.19  4982.0 2017.19  5004.7 2017.19  5005.3 2018.19
  5007.6 2021.10  5022.0 2025.29  5057.2 2024.96  5071.5 2028.27  5132.1 2029.96
  5184.9 2031.28  5237.1 2029.46  5277.5 2029.86  5284.0 2031.00  5291.9 2029.85
  5333.5 2029.03  5397.4 2030.78  5490.0 2030.62  5745.3 2033.79  5810.8 2033.83
  5817.3 2032.26  5838.1 2031.19  5860.4 2034.71  5881.2 2041.50  5888.4 2041.59
#Mann=7,-1,0
  4857.6   0.035       0  4939.1    0.07       0  4981.4    0.07       0
  5005.3    0.07       0  5132.1   0.035       0  5237.1    0.07       0
  5745.3    0.16       0
Bank Sta=4981.4,5005.3
Exp/Cntr=0.3,0.1

Type RM Length L Ch R = 1,12584,584,584,584
BEGIN DESCRIPTION:
Sweetwater Creek Trib 27 25.0
END DESCRIPTION:
XS GIS Cut Line= 3
      1391231.33      6870743.70      1390999.55      6870390.45
      1390004.97      6869437.97
#Sta/Elev= 30
  4577.5 2048.33  4672.5 2044.14  4702.7 2039.59  4946.8 2030.80  4961.9 2028.77
  4983.0 2018.43  4992.8 2016.87  4993.4 2015.87  5016.8 2016.87  5040.3 2020.83
  5047.5 2024.20  5056.8 2024.11  5118.0 2023.96  5181.8 2027.64  5450.4 2025.99
  5542.5 2031.02  5676.4 2032.02  5746.7 2033.18  5775.9 2032.38  5804.2 2039.82
  5818.4 2038.52  5839.4 2032.85  5901.1 2035.77  6118.8 2045.02  6143.5 2049.15
  6164.9 2048.54  6285.1 2055.33  6306.4 2052.87  6334.8 2053.73  6377.1 2057.03
#Mann=8,-1,0
  4577.5   0.035       0  4992.8   0.035       0  5016.8   0.035       0
  5056.8    0.07       0  5676.4    0.16       0  5746.7    0.07       0
  5901.1   0.035       0  6118.8    0.07       0
Bank Sta=4992.8,5016.8
Exp/Cntr=0.3,0.1

Type RM Length L Ch R = 1,12000,500,500,500
BEGIN DESCRIPTION:
Sweetwater Creek Trib 27 24.0
END DESCRIPTION:
XS GIS Cut Line= 3
      1391328.71      6870689.23      1390906.67      6869845.05
      1390854.99      6869487.96
#Sta/Elev= 30
  4056.2 2044.66  4080.6 2044.68  4103.0 2040.65  4147.7 2038.85  4164.5 2036.62
  4365.7 2029.20  4634.0 2026.79  4662.0 2027.94  4684.4 2026.99  4717.2 2027.91
  4908.0 2027.22  4930.3 2026.48  4945.5 2023.20  4952.7 2022.05  4963.2 2023.24
  4969.5 2021.86  4975.1 2018.55  4993.6 2016.62  4994.4 2015.62  5022.9 2015.62
  5023.6 2016.62  5037.4 2022.04  5049.6 2030.04  5067.7 2034.06  5108.2 2035.15
  5148.6 2033.79  5255.4 2033.74  5290.0 2038.74  5320.3 2035.88  5360.8 2038.49
#Mann=4,-1,0
  4056.2   0.035       0  4945.5    0.07       0  4993.6    0.07       0
  5023.6    0.07       0
Bank Sta=4993.6,5023.6
Exp/Cntr=0.3,0.1

Type RM Length L Ch R = 1,11500,500,500,500
BEGIN DESCRIPTION:
Sweetwater Creek Trib 27 23.0
END DESCRIPTION:
XS GIS Cut Line= 3
      1391405.00      6870738.00      1391375.11      6869767.86
      1391154.97      6869437.96
#Sta/Elev= 30
  4029.4 2048.23  4059.4 2045.45  4079.4 2045.37  4109.4 2039.97  4129.4 2039.34
  4149.5 2036.76  4279.5 2030.33  4520.5 2026.26  4959.8 2025.37  4969.8 2024.53
  4987.0 2015.18  4987.6 2014.18  5010.4 2014.18  5011.0 2015.18  5022.5 2019.05
  5028.6 2019.90  5035.9 2023.08  5065.2 2023.93  5075.7 2025.64  5079.6 2026.55
  5085.6 2026.20  5121.7 2031.51  5144.1 2033.89  5172.7 2034.72  5223.8 2034.12
  5286.9 2034.87  5324.4 2035.01  5338.0 2036.35  5383.0 2035.74  5396.6 2038.08
#Mann=6,-1,0
  4029.4   0.035       0  4987.0   0.035       0  5011.0   0.035       0
  5065.2    0.07       0  5075.7   0.035       0  5286.9    0.07       0
Bank Sta=4987,5011
Exp/Cntr=0.3,0.1

Type RM Length L Ch R = 1,11000,1764,1764,1764
BEGIN DESCRIPTION:
Sweetwater Creek Trib 27 22.0
END DESCRIPTION:
XS GIS Cut Line= 4
      1391529.54      6870924.65      1391696.03      6869620.22
      1391587.20      6869404.42      1391254.98      6869187.99
#Sta/Elev= 30
  3443.3 2066.40  3460.1 2062.46  3470.2 2064.79  3661.7 2039.18  3680.3 2041.03
  3702.0 2037.17  3760.2 2032.75  3840.0 2029.73  4448.0 2024.07  4649.7 2025.54
  4750.5 2023.74  4797.0 2025.56  4825.7 2023.12  4858.3 2020.28  4925.2 2022.83
  4969.8 2021.65  4992.1 2020.10  4995.4 2013.46  4995.8 2012.46  5013.4 2013.46
  5020.7 2019.84  5026.7 2021.32  5035.9 2029.64  5114.6 2030.78  5259.2 2034.27
  5280.2 2036.82  5289.1 2035.03  5337.6 2042.16  5392.8 2044.75  5396.5 2044.87
#Mann=6,-1,0
  3443.3   0.035       0  4825.7    0.07       0  4995.4    0.07       0
  5013.4    0.07       0  5114.6    0.07       0  5392.8   0.035       0
Bank Sta=4995.4,5013.4
Exp/Cntr=0.3,0.1

Type RM Length L Ch R = 1,9236,666,666,666
BEGIN DESCRIPTION:
Sweetwater Creek Trib 27 4176
END DESCRIPTION:
XS GIS Cut Line= 4
      1391880.72      6870816.89      1391998.35      6870494.69
      1392076.03      6869662.39      1391702.76      6869037.38
#Sta/Elev= 30
  4657.0 2051.54  4666.5 2050.90  4677.1 2047.36  4688.6 2050.72  4707.2 2050.72
  4736.9 2049.90  4861.2 2041.11  4886.9 2034.28  4891.8 2034.61  4900.7 2031.66
  4917.0 2018.98  4942.2 2016.45  4947.5 2017.94  4964.5 2013.17  4977.9 2011.95
  4978.7 2010.95  5007.9 2011.95  5014.8 2017.19  5019.8 2014.23  5036.8 2019.07
  5257.8 2024.58  5286.0 2023.98  5303.3 2024.07  5629.5 2027.83  5985.4 2028.42
  6038.0 2026.37  6234.5 2025.61  6320.1 2028.68  6526.3 2028.97  6563.9 2035.26
#Mann=9,-1,0
  4657.0    0.07       0  4707.2   0.035       0  4736.9    0.07       0
  4886.9    0.16       0  4977.9    0.07       0  5007.9    0.16       0
  5286.0    0.07       0  5303.3    0.16       0  5629.5    0.07       0
Bank Sta=4977.9,5007.9
Exp/Cntr=0.3,0.1

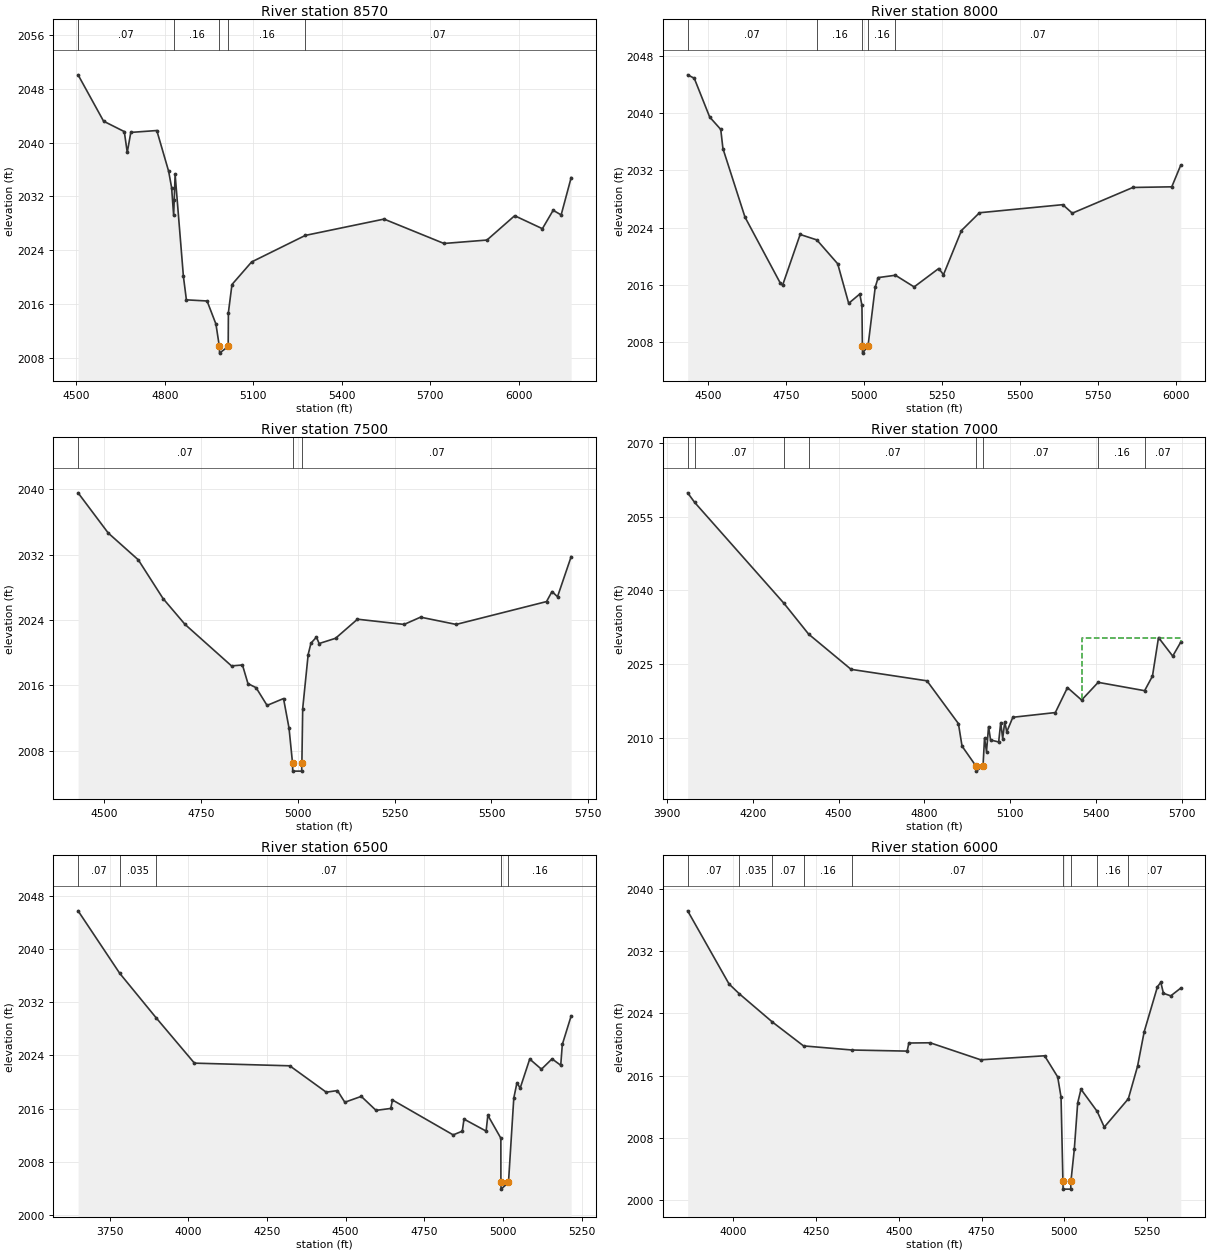
Type RM Length L Ch R = 1,8570,570,570,570
BEGIN DESCRIPTION:
Sweetwater Creek Trib 27 17.0
END DESCRIPTION:
XS GIS Cut Line= 3
      1392358.27      6870494.35      1392391.22      6870001.15
      1391759.59      6869007.64
#Sta/Elev= 30
  4505.7 2050.08  4592.2 2043.18  4662.4 2041.63  4672.4 2038.54  4684.5 2041.51
  4772.6 2041.79  4812.7 2035.73  4822.8 2033.29  4829.7 2029.15  4831.6 2031.47
  4834.7 2035.25  4862.8 2020.07  4872.9 2016.59  4943.0 2016.42  4973.1 2012.98
  4984.6 2009.66  4985.3 2008.66  5014.6 2009.66  5015.3 2014.70  5027.4 2018.87
  5094.0 2022.23  5276.1 2026.18  5542.9 2028.61  5746.1 2024.98  5891.8 2025.49
  5985.7 2029.11  6079.7 2027.18  6116.2 2029.92  6143.3 2029.23  6177.3 2034.79
#Mann=5,-1,0
  4505.7    0.07       0  4831.6    0.16       0  4984.6    0.07       0
  5014.6    0.16       0  5276.1    0.07       0
Bank Sta=4984.6,5014.6
Exp/Cntr=0.3,0.1

Type RM Length L Ch R = 1,8000,500,500,500
BEGIN DESCRIPTION:
Sweetwater Creek Trib 27 16.0
END DESCRIPTION:
XS GIS Cut Line= 3
      1393055.00      6869938.00      1392664.09      6869530.76
      1391804.99      6868987.99
#Sta/Elev= 30
  4435.5 2045.32  4456.7 2044.84  4506.1 2039.43  4541.6 2037.70  4548.6 2035.03
  4619.3 2025.46  4732.5 2016.25  4739.8 2015.95  4796.1 2023.04  4849.6 2022.28
  4916.5 2018.95  4951.7 2013.43  4987.3 2014.73  4994.2 2013.14  4995.7 2007.48
  4996.1 2006.48  5013.7 2007.48  5036.8 2015.69  5046.2 2017.02  5101.5 2017.35
  5161.5 2015.72  5240.3 2018.29  5255.6 2017.43  5313.2 2023.59  5370.9 2026.07
  5638.0 2027.20  5668.5 2026.01  5862.7 2029.60  5987.4 2029.69  6016.2 2032.72
#Mann=5,-1,0
  4435.5    0.07       0  4849.6    0.16       0  4995.7    0.07       0
  5013.7    0.16       0  5101.5    0.07       0
Bank Sta=4995.7,5013.7
Exp/Cntr=0.3,0.1

Type RM Length L Ch R = 1,7500,500,500,500
BEGIN DESCRIPTION:
Sweetwater Creek Trib 27 15.0
END DESCRIPTION:
XS GIS Cut Line= 3
      1393254.98      6869537.98      1392863.34      6869127.70
      1392355.03      6868638.03
#Sta/Elev= 30
  4432.8 2039.59  4510.6 2034.67  4588.3 2031.38  4652.2 2026.64  4708.8 2023.48
  4828.9 2018.39  4857.2 2018.50  4871.4 2016.22  4892.4 2015.72  4920.7 2013.55
  4963.2 2014.39  4977.4 2010.77  4986.4 2006.50  4987.0 2005.50  5010.0 2005.50
  5010.6 2006.50  5012.7 2013.17  5026.8 2019.78  5034.0 2021.17  5048.2 2021.92
  5055.1 2021.13  5097.5 2021.77  5154.1 2024.11  5274.5 2023.47  5317.0 2024.36
  5408.8 2023.47  5642.2 2026.27  5656.3 2027.50  5670.5 2026.86  5705.8 2031.78
#Mann=3,-1,0
  4432.8    0.07       0  4986.4    0.07       0  5010.6    0.07       0
Bank Sta=4986.4,5010.6
Exp/Cntr=0.3,0.1

Type RM Length L Ch R = 1,7000,500,500,500
BEGIN DESCRIPTION:
Sweetwater Creek Trib 27 14.0
END DESCRIPTION:
XS GIS Cut Line= 3
      1393555.01      6869788.02      1393205.70      6868821.93
      1392705.03      6868338.03
#Sta/Elev= 30
  3972.7 2059.90  3997.0 2057.96  4308.8 2037.41  4395.6 2031.09  4543.9 2023.91
  4809.2 2021.57  4919.1 2012.85  4931.8 2008.26  4980.9 2004.16  4981.5 2003.16
  5005.1 2004.16  5010.4 2009.89  5017.3 2007.14  5024.5 2012.24  5031.5 2009.52
  5059.8 2009.10  5067.0 2013.05  5073.9 2009.81  5081.1 2013.24  5088.1 2011.17
  5109.4 2014.14  5257.9 2015.10  5300.3 2020.19  5349.7 2017.65  5407.6 2021.26
  5569.9 2019.56  5597.4 2022.53  5618.5 2030.39  5668.2 2026.61  5696.3 2029.46
#Mann=8,-1,0
  3972.7   0.035       0  3997.0    0.07       0  4308.8   0.035       0
  4395.6    0.07       0  4980.9    0.07       0  5005.1    0.07       0
  5407.6    0.16       0  5569.9    0.07       0
#XS Ineff=2,0
       0                 5351.60    0.00 2030.26
Permanent Ineff=
       F       F
Bank Sta=4980.9,5005.1
Exp/Cntr=0.3,0.1

Type RM Length L Ch R = 1,6500,500,500,500
BEGIN DESCRIPTION:
Sweetwater Creek Trib 27 13.0
END DESCRIPTION:
XS GIS Cut Line= 3
      1393607.86      6869611.31      1393069.20      6868373.11
      1392854.96      6868337.99
#Sta/Elev= 30
  3649.7 2045.71  3782.1 2036.33  3898.6 2029.61  4019.5 2022.85  4322.6 2022.45
  4438.5 2018.49  4474.1 2018.73  4497.6 2016.98  4549.9 2017.86  4596.8 2015.76
  4643.6 2016.05  4649.1 2017.32  4842.0 2012.08  4871.0 2012.64  4876.4 2014.45
  4946.7 2012.65  4952.2 2015.02  4993.6 2011.58  4993.7 2004.94  4994.3 2003.94
  5017.8 2004.94  5034.7 2017.61  5044.8 2019.91  5054.9 2019.09  5085.3 2023.46
  5122.6 2021.94  5156.3 2023.49  5183.9 2022.53  5188.9 2025.65  5217.1 2029.95
#Mann=5,-1,0
  3649.7    0.07       0  3782.1   0.035       0  3898.6    0.07       0
  4993.7    0.07       0  5017.8    0.16       0
Bank Sta=4993.7,5017.8
Exp/Cntr=0.3,0.1

Type RM Length L Ch R = 1,6000,500,500,500
BEGIN DESCRIPTION:
Sweetwater Creek Trib 27 12.0
END DESCRIPTION:
XS GIS Cut Line= 3
      1393708.84      6869514.27      1393540.61      6868388.47
      1393505.00      6868037.98
#Sta/Elev= 30
  3861.7 2037.19  3986.8 2027.79  4017.5 2026.54  4117.8 2022.90  4212.0 2019.83
  4358.9 2019.30  4525.3 2019.16  4530.4 2020.20  4594.6 2020.23  4747.7 2018.04
  4940.7 2018.56  4980.3 2015.84  4990.4 2013.25  4996.1 2002.42  4996.7 2001.42
  5019.7 2001.42  5020.3 2002.42  5030.6 2006.59  5040.7 2012.50  5050.7 2014.26
  5099.8 2011.40  5121.1 2009.39  5193.8 2013.03  5221.6 2017.20  5241.7 2021.64
  5281.9 2027.44  5292.0 2028.00  5299.9 2026.59  5322.1 2026.26  5352.3 2027.26
#Mann=9,-1,0
  3861.7    0.07       0  4017.5   0.035       0  4117.8    0.07       0
  4212.0    0.16       0  4358.9    0.07       0  4996.1    0.07       0
  5020.3    0.07       0  5099.8    0.16       0  5193.8    0.07       0
Bank Sta=4996.1,5020.3
Exp/Cntr=0.3,0.1

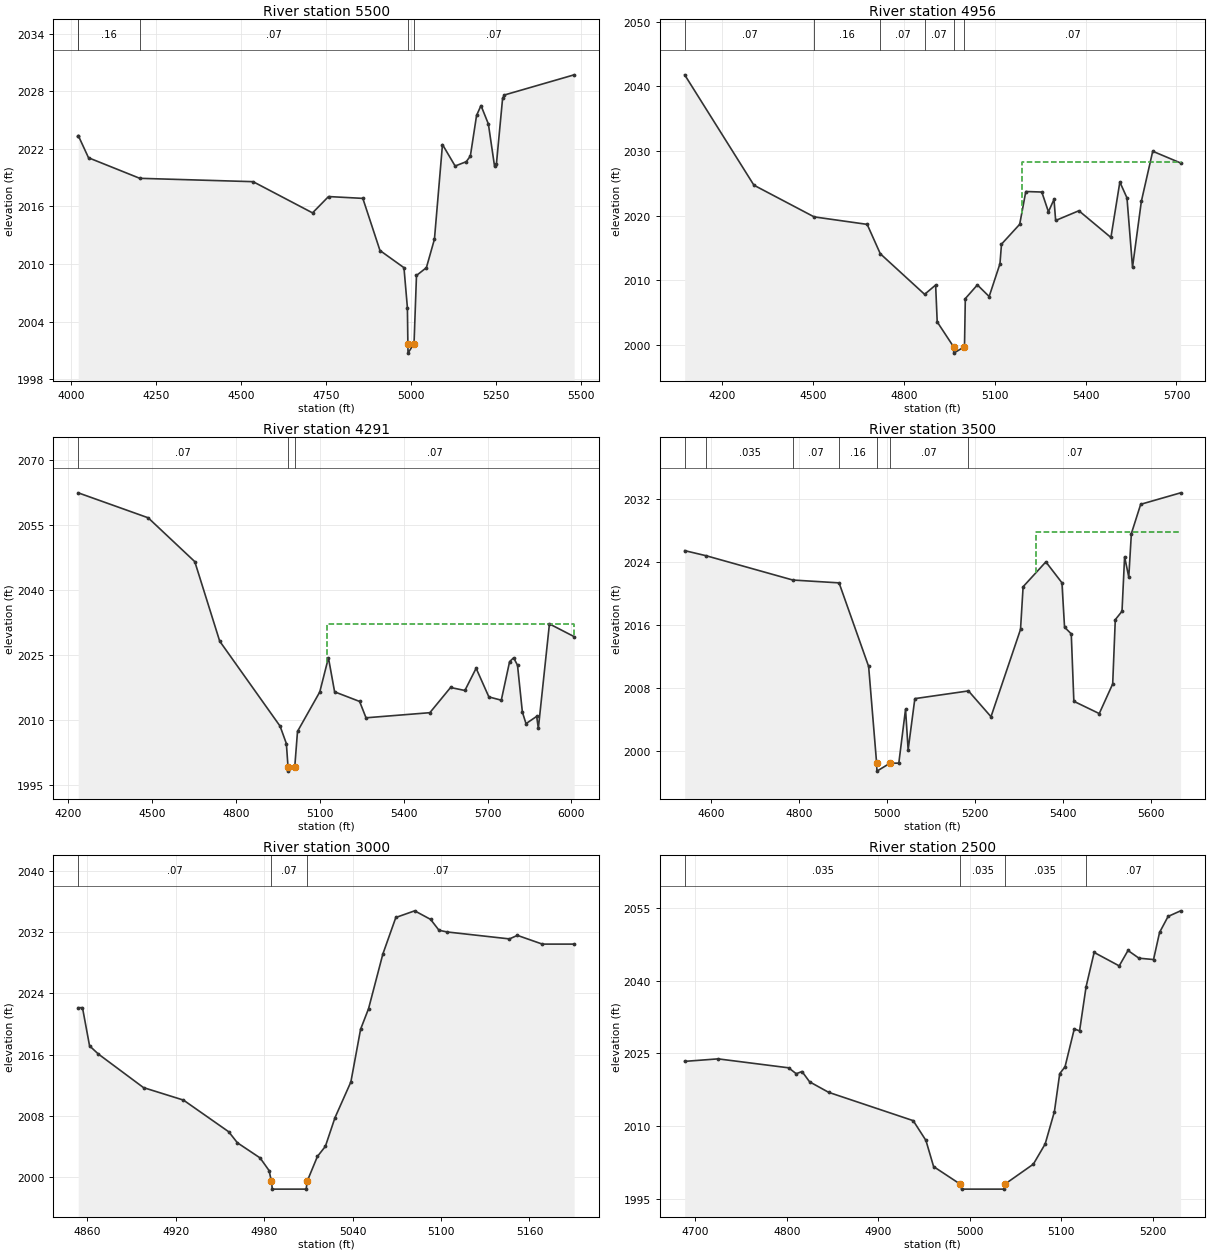
Type RM Length L Ch R = 1,5500,544,544,544
BEGIN DESCRIPTION:
Sweetwater Creek Trib 27 11.0
END DESCRIPTION:
XS GIS Cut Line= 3
      1393854.99      6869238.05      1393976.11      6868266.67
      1393789.46      6867825.86
#Sta/Elev= 30
  4021.1 2023.34  4021.7 2023.34  4051.4 2021.06  4202.0 2018.92  4535.1 2018.57
  4709.8 2015.32  4756.8 2017.02  4857.6 2016.83  4908.0 2011.40  4978.5 2009.61
  4988.6 2005.45  4990.0 2001.71  4990.4 2000.71  5008.1 2001.71  5008.2 2001.79
  5015.3 2008.80  5044.4 2009.61  5068.1 2012.58  5091.7 2022.44  5128.9 2020.20
  5161.4 2020.65  5173.6 2021.23  5191.9 2025.47  5204.9 2026.50  5226.6 2024.58
  5244.7 2020.19  5250.1 2020.36  5268.4 2027.25  5273.8 2027.60  5478.7 2029.70
#Mann=5,-1,0
  4021.1    0.07       0  4021.7    0.16       0  4202.0    0.07       0
  4990.0    0.07       0  5008.2    0.07       0
Bank Sta=4990,5008.1
Exp/Cntr=0.3,0.1

Type RM Length L Ch R = 1,4956,665,665,665
BEGIN DESCRIPTION:
Sweetwater Creek Trib 27 10.0
END DESCRIPTION:
XS GIS Cut Line= 4
      1394004.99      6869488.02      1394255.01      6868599.01
      1394287.52      6868345.62      1394109.97      6867923.07
#Sta/Elev= 30
  4076.5 2041.80  4305.1 2024.70  4503.9 2019.79  4679.0 2018.63  4722.3 2014.08
  4868.6 2007.79  4905.0 2009.23  4910.2 2003.52  4964.0 1999.68  4964.9 1998.68
  5000.3 1999.68  5003.0 2007.13  5042.8 2009.25  5081.7 2007.45  5117.4 2012.53
  5122.4 2015.56  5182.5 2018.64  5202.7 2023.72  5255.5 2023.64  5277.4 2020.58
  5295.8 2022.50  5301.2 2019.23  5377.9 2020.74  5483.7 2016.60  5513.2 2025.19
  5536.7 2022.73  5555.0 2011.99  5584.2 2022.20  5621.7 2029.96  5713.8 2028.14
#Mann=6,-1,0
  4076.5    0.07       0  4503.9    0.16       0  4722.3    0.07       0
  4868.6    0.07       0  4964.0    0.07       0  5000.3    0.07       0
#XS Ineff=2,0
       0                 5188.70    0.00 2028.31
Permanent Ineff=
       F       F
Bank Sta=4964,5000.3
Exp/Cntr=0.3,0.1

Type RM Length L Ch R = 1,4291,791,791,791
BEGIN DESCRIPTION:
Sweetwater Creek Trib 27 9.0
END DESCRIPTION:
XS GIS Cut Line= 3
      1394978.27      6869522.01      1394640.96      6868836.73
      1394213.02      6867921.99
#Sta/Elev= 30
  4236.2 2062.50  4486.4 2056.74  4653.1 2046.63  4742.2 2028.29  4958.2 2008.68
  4980.7 2004.65  4986.5 1999.31  4987.1 1998.31  5010.7 1999.31  5020.5 2007.47
  5100.1 2016.57  5131.1 2024.46  5153.2 2016.60  5242.6 2014.38  5265.5 2010.61
  5493.9 2011.79  5567.9 2017.60  5619.1 2016.91  5659.3 2022.04  5704.9 2015.43
  5749.3 2014.67  5779.0 2023.56  5793.5 2024.45  5807.3 2022.74  5824.7 2011.94
  5837.7 2009.26  5875.9 2010.94  5881.8 2008.16  5921.5 2032.27  6009.9 2029.33
#Mann=3,-1,0
  4236.2    0.07       0  4986.5    0.07       0  5010.7    0.07       0
#XS Ineff=2,0
       0                 5126.10    0.00 2032.33
Permanent Ineff=
       F       F
Bank Sta=4986.5,5010.7
Exp/Cntr=0.3,0.1

Type RM Length L Ch R = 1,3500,500,500,500
BEGIN DESCRIPTION:
Sweetwater Creek Trib 27 7.0
END DESCRIPTION:
XS GIS Cut Line= 3
      1395271.91      6868495.21      1394842.99      6868326.79
      1394276.77      6867972.36
#Sta/Elev= 30
  4539.2 2025.42  4588.1 2024.77  4785.4 2021.68  4890.6 2021.32  4957.9 2010.69
  4976.1 1998.38  4976.8 1997.38  5006.3 1998.38  5026.6 1998.40  5041.9 2005.25
  5047.8 2000.09  5063.1 2006.60  5185.1 2007.58  5236.4 2004.30  5303.6 2015.40
  5309.5 2020.83  5361.3 2023.99  5397.9 2021.33  5403.8 2015.69  5419.1 2014.83
  5425.0 2006.26  5482.8 2004.70  5513.4 2008.47  5519.3 2016.64  5534.6 2017.71
  5540.5 2024.65  5550.0 2022.05  5555.9 2027.59  5577.1 2031.31  5668.0 2032.77
#Mann=7,-1,0
  4539.2    0.07       0  4588.1   0.035       0  4785.4    0.07       0
  4890.6    0.16       0  4976.1    0.07       0  5006.3    0.07       0
  5185.1    0.07       0
#XS Ineff=2,0
       0                 5339.10    0.00 2027.79
Permanent Ineff=
       F       F
Bank Sta=4976.1,5006.3
Exp/Cntr=0.3,0.1

Type RM Length L Ch R = 1,3000,500,500,500
BEGIN DESCRIPTION:
Sweetwater Creek Trib 27 6.0
END DESCRIPTION:
XS GIS Cut Line= 3
      1394805.00      6867988.00      1394680.86      6867910.79
      1394505.02      6867838.01
#Sta/Elev= 30
  4853.8 2022.14  4856.7 2022.14  4861.5 2017.15  4867.4 2016.09  4898.1 2011.69
  4925.2 2010.06  4955.9 2005.92  4961.8 2004.48  4977.2 2002.50  4983.3 2000.85
  4984.9 1999.42  4985.5 1998.42  5008.5 1998.42  5009.1 1999.42  5016.1 2002.69
  5021.5 2004.01  5028.0 2007.75  5038.8 2012.43  5045.4 2019.32  5050.8 2022.01
  5060.5 2029.15  5069.3 2033.93  5082.1 2034.80  5092.9 2033.68  5098.6 2032.26
  5104.0 2032.04  5146.4 2031.13  5151.8 2031.59  5168.7 2030.45  5190.3 2030.45
#Mann=3,-1,0
  4853.8    0.07       0  4984.9    0.07       0  5009.1    0.07       0
Bank Sta=4984.9,5009.1
Exp/Cntr=0.3,0.1

Type RM Length L Ch R = 1,2500,500,500,500
BEGIN DESCRIPTION:
Sweetwater Creek Trib 27 5.0
END DESCRIPTION:
XS GIS Cut Line= 3
      1394955.01      6868137.99      1395141.59      6867888.42
      1395255.01      6867687.99
#Sta/Elev= 30
  4688.4 2023.34  4724.9 2023.86  4802.0 2022.01  4810.3 2020.79  4816.6 2021.25
  4824.9 2019.12  4845.7 2016.95  4938.1 2011.10  4952.0 2007.02  4960.4 2001.61
  4989.7 1997.96  4990.9 1996.96  5036.9 1996.96  5038.1 1997.96  5069.4 2002.12
  5082.3 2006.29  5092.4 2012.97  5098.2 2020.81  5104.0 2022.22  5114.1 2030.04
  5119.9 2029.64  5127.0 2038.75  5135.8 2045.84  5163.2 2043.06  5172.8 2046.24
  5184.8 2044.65  5200.7 2044.37  5207.3 2049.97  5216.6 2053.27  5230.3 2054.43
#Mann=4,-1,0
  4688.4   0.035       0  4989.7   0.035       0  5038.1   0.035       0
  5127.0    0.07       0
Bank Sta=4989.7,5038.1
Exp/Cntr=0.3,0.1

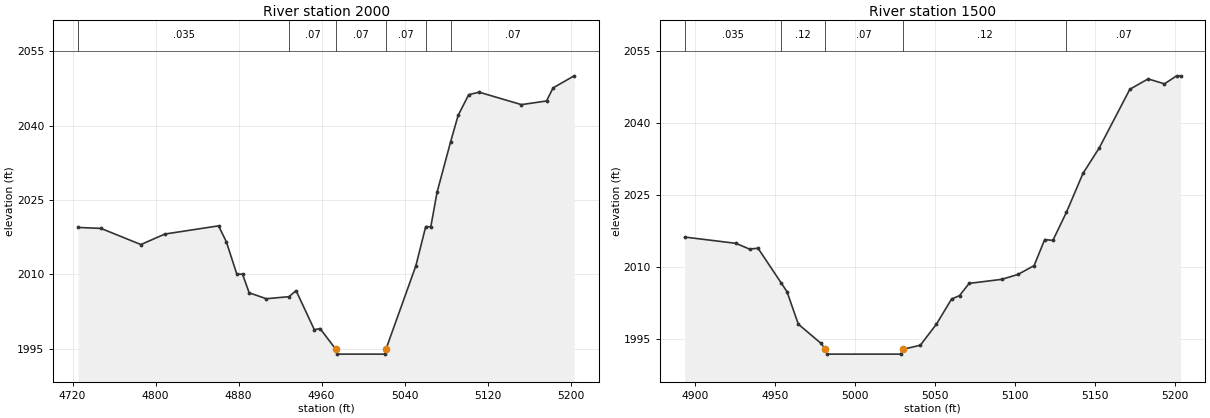
Type RM Length L Ch R = 1,2000,500,500,500
BEGIN DESCRIPTION:
Sweetwater Creek Trib 27 4.0
END DESCRIPTION:
XS GIS Cut Line= 3
      1395754.99      6868137.99      1395641.59      6867888.01
      1395605.00      6867688.03
#Sta/Elev= 30
  4725.5 2019.45  4747.4 2019.26  4785.9 2016.00  4809.0 2018.12  4860.7 2019.77
  4868.2 2016.57  4878.3 2010.04  4883.8 2010.03  4890.2 2006.27  4906.8 2005.07
  4928.5 2005.49  4935.4 2006.70  4953.0 1998.82  4958.5 1999.06  4973.6 1994.90
  4974.8 1993.90  5020.8 1993.90  5022.0 1994.90  5050.8 2011.71  5060.3 2019.63
  5065.2 2019.58  5071.2 2026.53  5084.2 2036.66  5091.5 2042.03  5101.7 2046.23
  5111.8 2046.73  5152.5 2044.22  5176.7 2044.96  5183.0 2047.60  5203.3 2050.03
#Mann=6,-1,0
  4725.5   0.035       0  4928.5    0.07       0  4973.6    0.07       0
  5022.0    0.07       0  5060.3    0.12       0  5084.2    0.07       0
Bank Sta=4973.6,5022
Exp/Cntr=0.3,0.1

Type RM Length L Ch R = 1,1500,500,500,500
BEGIN DESCRIPTION:
Sweetwater Creek Trib 27 3.0
END DESCRIPTION:
XS GIS Cut Line= 3
      1396104.99      6867988.02      1396141.59      6867888.01
      1396105.00      6867688.03
#Sta/Elev= 30
  4893.5 2016.26  4925.5 2014.95  4934.0 2013.75  4939.3 2013.94  4953.8 2006.70
  4957.4 2004.89  4964.5 1998.12  4978.7 1994.11  4981.4 1992.88  4982.6 1991.88
  5028.6 1991.88  5029.8 1992.88  5040.7 1993.73  5050.8 1998.14  5060.2 2003.34
  5065.2 2004.07  5071.2 2006.61  5091.5 2007.45  5101.7 2008.47  5111.8 2010.32
  5118.4 2015.74  5123.5 2015.56  5132.0 2021.44  5142.3 2029.51  5152.5 2034.84
  5171.6 2047.04  5183.0 2049.19  5193.2 2048.16  5200.8 2049.83  5203.3 2049.83
#Mann=5,-1,0
  4893.5   0.035       0  4953.8    0.12       0  4981.4    0.07       0
  5029.8    0.12       0  5132.0    0.07       0
Bank Sta=4981.4,5029.8
Exp/Cntr=0.3,0.1