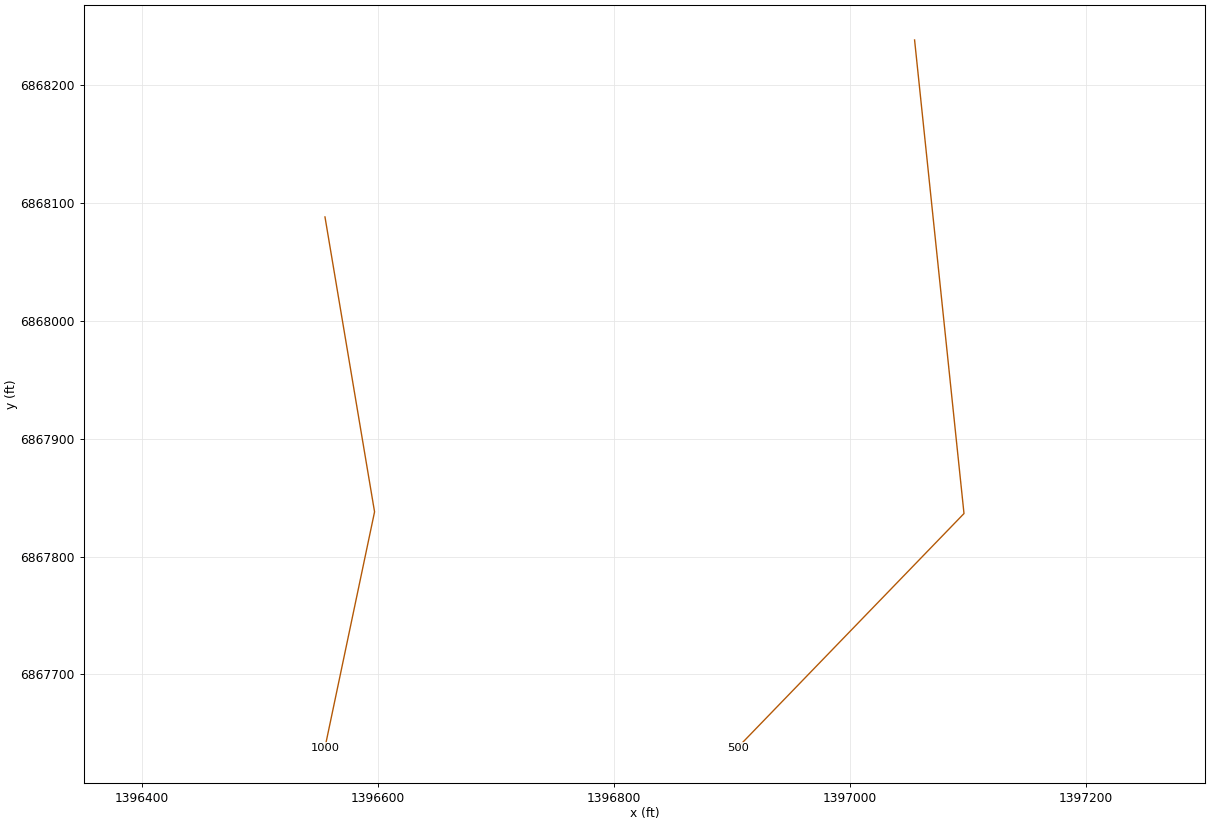
HEC-RAS study Sweetwater Creek Trib 27.prj: Sweetwater Creek Trib 27 Base Level Engineering

--- Sweetwater Creek Trib 27.g01 (geometry) --- (continued)

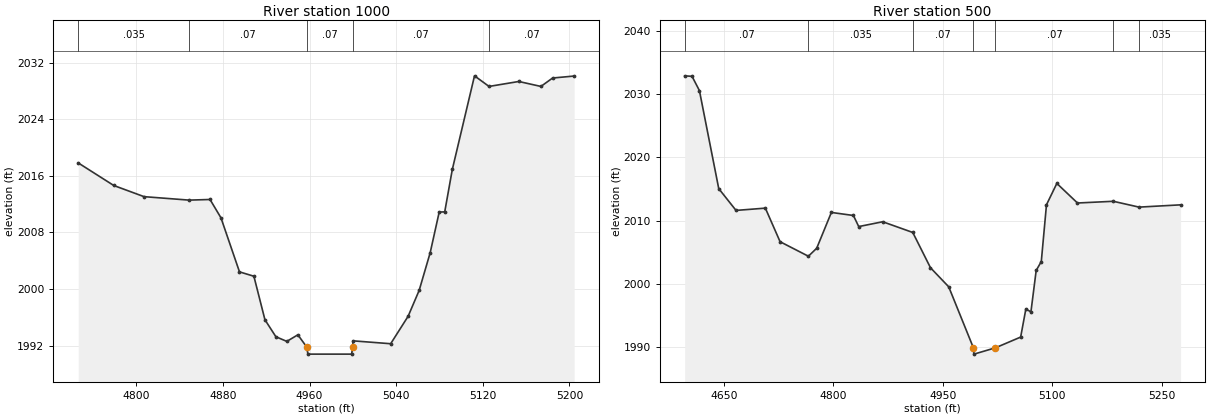
Type RM Length L Ch R = 1,1000,500,500,500
BEGIN DESCRIPTION:
Sweetwater Creek Trib 27 2.0
END DESCRIPTION:
XS GIS Cut Line= 3
      1396555.00      6868087.97      1396597.05      6867837.88
      1396554.99      6867637.96
#Sta/Elev= 30
  4746.4 2017.83  4779.2 2014.64  4807.2 2013.06  4848.8 2012.57  4868.1 2012.66
  4878.2 2010.07  4895.3 2002.43  4908.6 2001.81  4918.8 1995.66  4928.9 1993.26
  4939.0 1992.60  4949.2 1993.53  4957.4 1991.80  4958.5 1990.80  4998.8 1990.80
  4999.9 1991.80  5000.0 1992.68  5034.9 1992.27  5051.0 1996.15  5061.2 1999.81
  5071.4 2005.15  5079.7 2010.88  5084.8 2010.91  5091.8 2016.90  5112.3 2030.14
  5125.7 2028.64  5153.2 2029.34  5173.6 2028.64  5184.4 2029.83  5204.3 2030.11
#Mann=5,-1,0
  4746.4   0.035       0  4848.8    0.07       0  4957.4    0.07       0
  4999.9    0.07       0  5125.7    0.07       0
Bank Sta=4957.4,4999.9
Exp/Cntr=0.3,0.1

Type RM Length L Ch R = 1,500,0,0,0
BEGIN DESCRIPTION:
Sweetwater Creek Trib 27 1.0
END DESCRIPTION:
XS GIS Cut Line= 3
      1397055.00      6868238.04      1397096.91      6867836.43
      1396904.97      6867637.97
#Sta/Elev= 30
  4596.2 2032.87  4606.3 2032.79  4616.4 2030.54  4642.9 2015.07  4666.6 2011.63
  4706.8 2011.99  4727.0 2006.69  4765.8 2004.40  4777.2 2005.66  4797.3 2011.31
  4827.5 2010.83  4834.8 2009.08  4867.7 2009.84  4908.9 2008.15  4933.2 2002.58
  4958.2 1999.57  4992.0 1989.95  4992.8 1988.95  5022.3 1989.95  5056.8 1991.64
  5063.9 1996.05  5070.9 1995.63  5078.1 2002.16  5085.1 2003.56  5092.2 2012.52
  5106.4 2015.89  5134.7 2012.80  5183.8 2013.07  5219.1 2012.15  5276.1 2012.51
#Mann=7,-1,0
  4596.2    0.07       0  4765.8   0.035       0  4908.9    0.07       0
  4992.0    0.07       0  5022.3    0.07       0  5183.8    0.07       0
  5219.1   0.035       0
Bank Sta=4992,5022.3
Exp/Cntr=0.3,0.1

Chan Stop Cuts=-1