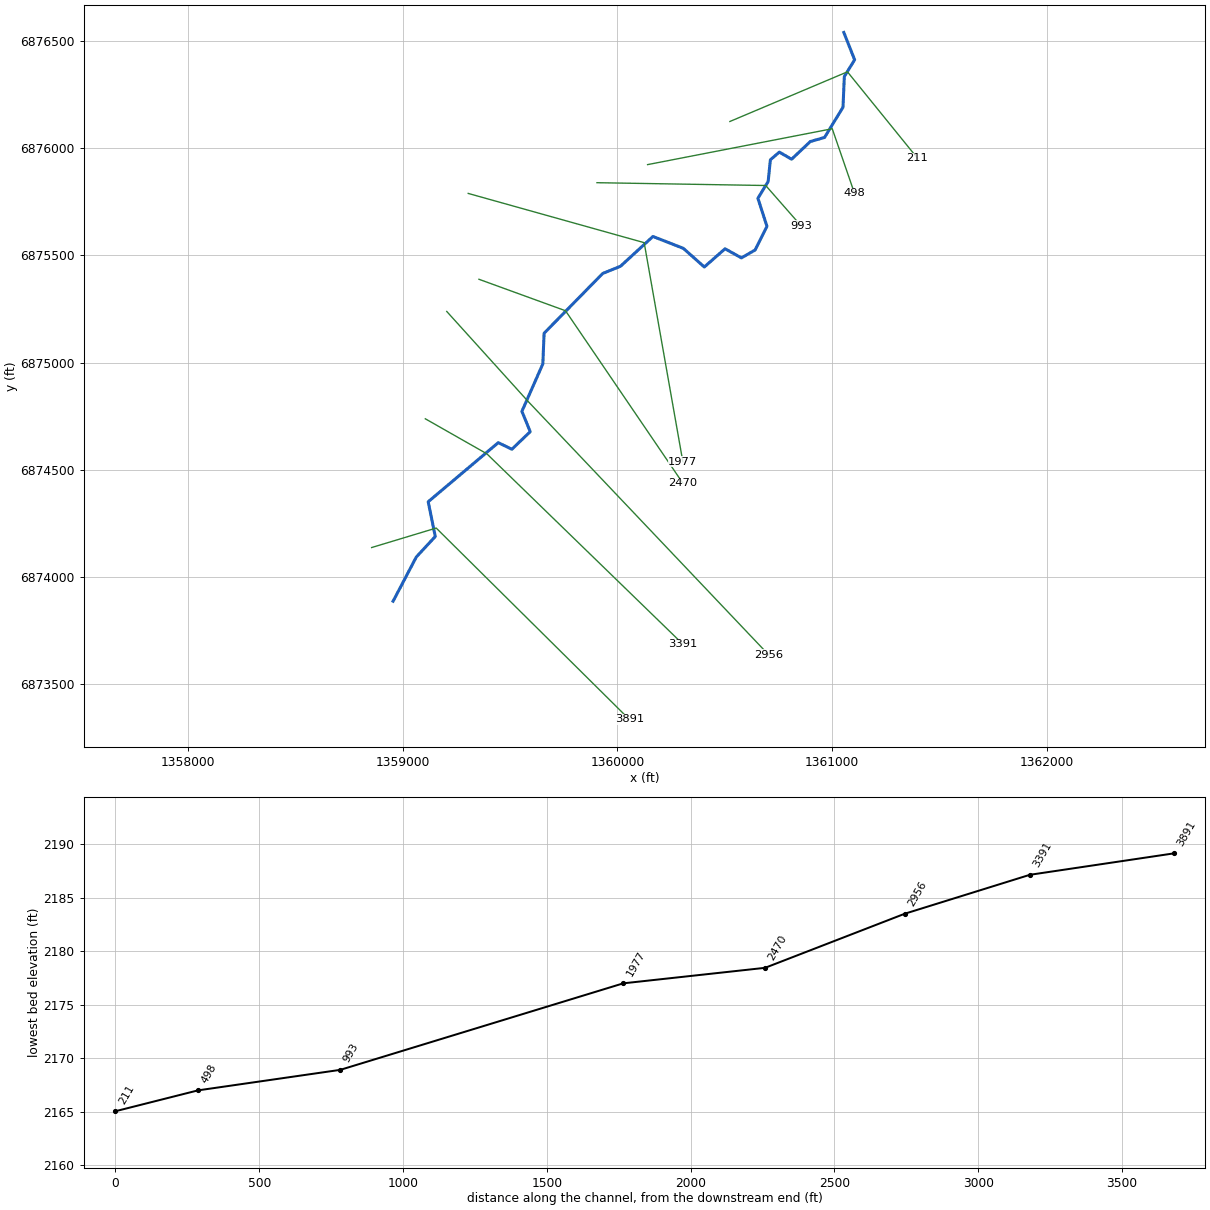
--- Sweetwater Creek Trib 27 T1.prj (project) ---

Proj Title=Sweetwater Creek Trib 27 T1 Base Level Engineering
Current Plan=p01
Default Exp/Contr=0.3,0.1
English Units
Geom File=g01
Flow File=f01
Plan File=p01
BEGIN DESCRIPTION:
Sweetwater Creek Trib 27 T1
END DESCRIPTION:

--- Sweetwater Creek Trib 27 T1.p01 (plan) ---

Plan Title=Multiple Run
Short Identifier=Multiple
Geom File=g01
Flow File=f01
Subcritical Flow
K Sum by GR= 0
Std Step Tol= 0.01
Critical Tol= 0.01
Num of Std Step Trials= 20
Max Error Tol= 0.3
Flow Tol Ratio= 0.001
Split Flow NTrial= 30
Split Flow Tol= 0.02
Split Flow Ratio= 0.02
Log Output Level= 0
Friction Slope Method= 1
Unsteady Friction Slope Method= 2
Unsteady Bridges Friction Slope Method= 1
Parabolic Critical Depth
Global Vel Dist=  1 , 1 , 1
Global Log Level= 0
CheckData=True
Encroach Param= -1, 0, 0, 0
BEGIN DESCRIPTION:
Multiple Run
END DESCRIPTION:

--- Sweetwater Creek Trib 27 T1.f01 (steady flow) ---

Flow Title=Multiple
Number of Profiles=7
Profile Names=10-year,25-year,50-year,1pct_min,100-year,1pct_plu,500-year
River Rch & RM= Sweetwater Creek,Reach-1,3891
     302     439     556     351     700    1397    1127
River Rch & RM= Sweetwater Creek,Reach-1,2956
     392     576     736     467     933    1861    1520
Boundary for River Rch & Prof#=Sweetwater Creek,Reach-1,1
Up Type=0
Dn Type=3
Dn Slope=0.005
Boundary for River Rch & Prof#=Sweetwater Creek,Reach-1,2
Up Type=0
Dn Type=3
Dn Slope=0.005
Boundary for River Rch & Prof#=Sweetwater Creek,Reach-1,3
Up Type=0
Dn Type=3
Dn Slope=0.005
Boundary for River Rch & Prof#=Sweetwater Creek,Reach-1,4
Up Type=0
Dn Type=3
Dn Slope=0.005
Boundary for River Rch & Prof#=Sweetwater Creek,Reach-1,5
Up Type=0
Dn Type=3
Dn Slope=0.005
Boundary for River Rch & Prof#=Sweetwater Creek,Reach-1,6
Up Type=0
Dn Type=3
Dn Slope=0.005
Boundary for River Rch & Prof#=Sweetwater Creek,Reach-1,7
Up Type=0
Dn Type=3
Dn Slope=0.005

--- Sweetwater Creek Trib 27 T1.g01 (geometry) ---

Geom Title=Existing Conditions

River Reach=Sweetwater Creek,Reach-1
Reach XY= 30
      1358955.00      6873888.00      1359063.16      6874094.05
      1359151.53      6874189.50      1359118.53      6874351.38
      1359445.00      6874626.76      1359508.36      6874596.00
      1359593.89      6874677.90      1359555.15      6874772.58
      1359652.61      6874993.53      1359658.54      6875136.53
      1359931.53      6875414.98      1360014.68      6875448.78
      1360165.62      6875587.41      1360307.30      6875532.14
      1360405.00      6875445.11      1360501.59      6875530.15
      1360577.88      6875487.61      1360641.54      6875524.30
      1360696.96      6875634.68      1360654.73      6875765.23
      1360702.52      6875843.58      1360712.86      6875944.80
      1360754.76      6875980.54      1360811.65      6875947.32
      1360898.97      6876029.80      1360965.00      6876048.65
      1361051.24      6876189.56      1361057.41      6876332.48
      1361105.44      6876410.80      1361055.00      6876538.00

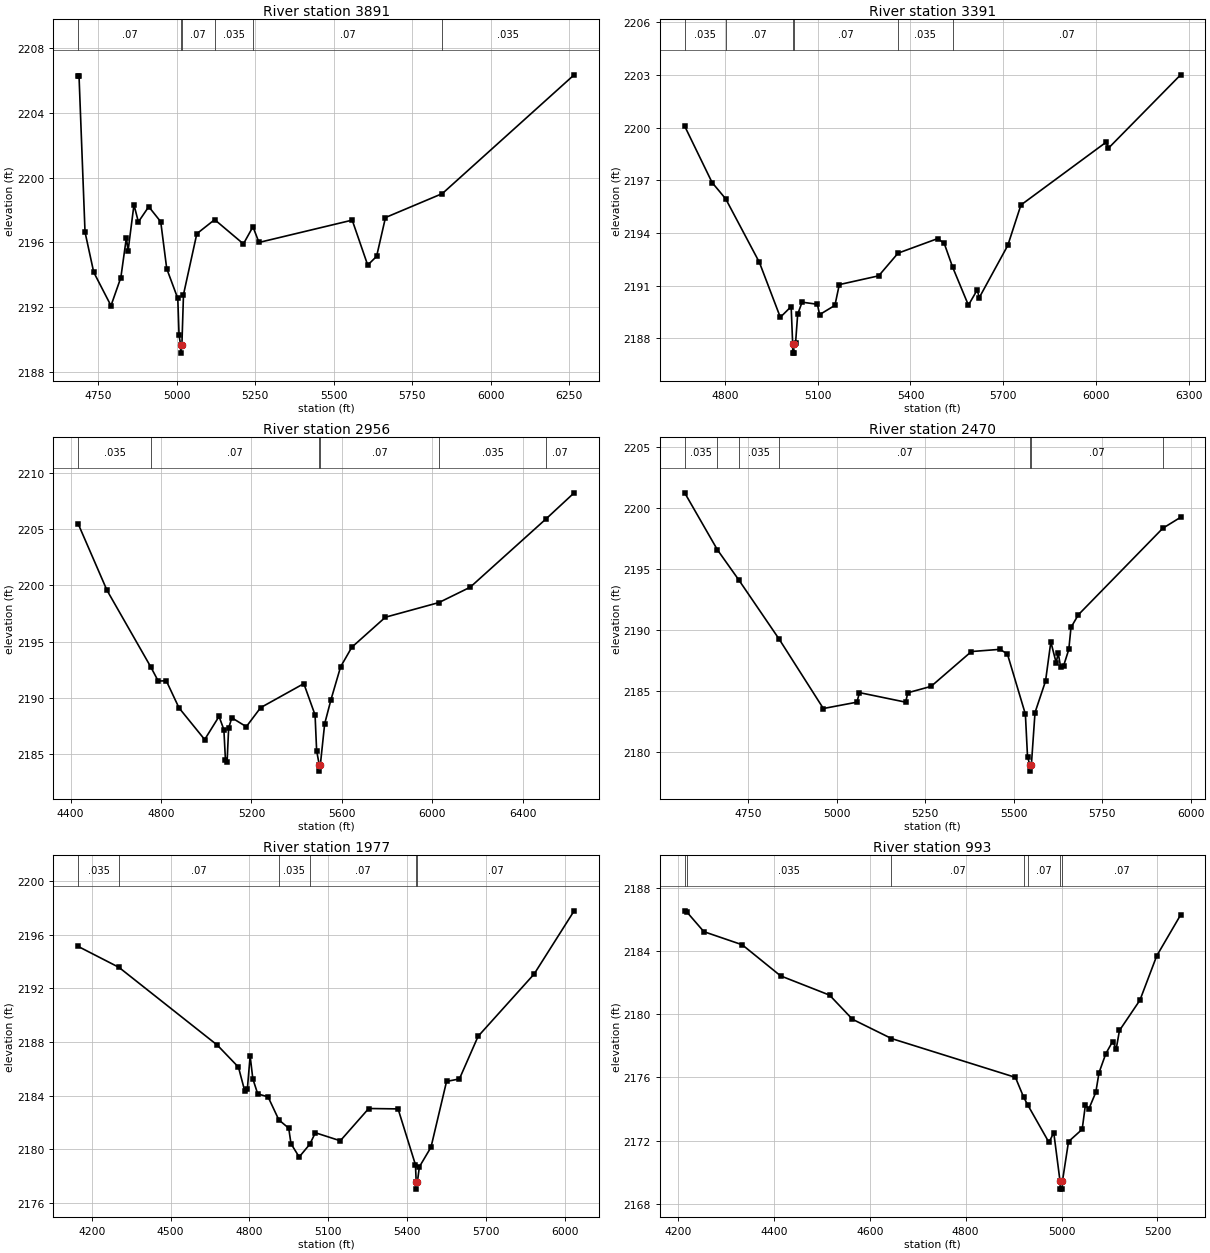
Type RM Length L Ch R = 1,3891,500,500,500
BEGIN DESCRIPTION:
Sweetwater Creek Trib 27 T1 6.0
END DESCRIPTION:
XS GIS Cut Line= 3
      1358855.03      6874138.01      1359155.81      6874228.85
      1360055.03      6873337.98
#Sta/Elev= 30
  4685.8 2206.28  4688.4 2206.28  4707.5 2196.64  4735.2 2194.16  4790.2 2192.09
  4821.6 2193.83  4839.3 2196.30  4844.6 2195.47  4863.4 2198.33  4877.5 2197.27
  4910.5 2198.21  4948.7 2197.28  4967.8 2194.38  5003.0 2192.54  5007.1 2190.26
  5012.1 2189.66  5012.4 2189.16  5016.1 2189.66  5021.2 2192.78  5063.7 2196.54
  5120.5 2197.41  5212.1 2195.91  5242.5 2196.97  5261.7 2196.00  5558.7 2197.38
  5608.1 2194.60  5636.4 2195.14  5664.7 2197.54  5845.8 2199.02  6265.8 2206.36
#Mann=6,-1,0
  4685.8    0.07       0  5012.1    0.07       0  5016.1    0.07       0
  5120.5   0.035       0  5242.5    0.07       0  5845.8   0.035       0
Bank Sta=5012.1,5016.1
Exp/Cntr=0.3,0.1

Type RM Length L Ch R = 1,3391,435,435,435
BEGIN DESCRIPTION:
Sweetwater Creek Trib 27 T1 5.0
END DESCRIPTION:
XS GIS Cut Line= 3
      1359105.03      6874737.98      1359391.68      6874574.87
      1360305.02      6873687.98
#Sta/Elev= 30
  4670.2 2200.08  4758.8 2196.87  4802.8 2195.94  4911.8 2192.32  4979.3 2189.20
  5014.3 2189.81  5019.3 2187.66  5019.5 2187.16  5023.0 2187.16  5023.3 2187.66
  5028.5 2187.72  5035.4 2189.37  5049.6 2190.06  5099.2 2189.94  5106.2 2189.35
  5155.8 2189.88  5169.9 2191.06  5297.3 2191.56  5359.8 2192.85  5488.1 2193.68
  5509.2 2193.40  5536.1 2192.06  5587.2 2189.89  5615.5 2190.75  5622.4 2190.32
  5714.5 2193.29  5756.9 2195.59  6032.7 2199.17  6039.6 2198.82  6273.1 2203.00
#Mann=6,-1,0
  4670.2   0.035       0  4802.8    0.07       0  5019.3    0.07       0
  5023.3    0.07       0  5359.8   0.035       0  5536.1    0.07       0
Bank Sta=5019.3,5023.3
Exp/Cntr=0.3,0.1

Type RM Length L Ch R = 1,2956,486,486,486
BEGIN DESCRIPTION:
Sweetwater Creek Trib 27 T1 4.0
END DESCRIPTION:
XS GIS Cut Line= 3
      1359205.03      6875237.97      1359584.78      6874818.00
      1360705.03      6873637.97
#Sta/Elev= 30
  4433.8 2205.44  4561.2 2199.55  4754.4 2192.77  4787.6 2191.51  4823.4 2191.53
  4879.5 2189.13  4993.1 2186.32  5056.6 2188.37  5078.0 2187.20  5084.9 2184.51
  5092.2 2184.33  5099.1 2187.34  5113.2 2188.25  5177.1 2187.46  5240.6 2189.15
  5431.6 2191.28  5481.3 2188.50  5488.2 2185.33  5500.3 2184.02  5500.6 2183.52
  5504.3 2184.02  5523.8 2187.72  5551.7 2189.86  5594.2 2192.77  5643.9 2194.51
  5792.4 2197.17  6029.2 2198.47  6167.3 2199.83  6504.5 2205.92  6627.1 2208.20
#Mann=6,-1,0
  4433.8   0.035       0  4754.4    0.07       0  5500.3    0.07       0
  5504.3    0.07       0  6029.2   0.035       0  6504.5    0.07       0
Bank Sta=5500.3,5504.3
Exp/Cntr=0.3,0.1

Type RM Length L Ch R = 1,2470,493,493,493
BEGIN DESCRIPTION:
Sweetwater Creek Trib 27 T1 3.0
END DESCRIPTION:
XS GIS Cut Line= 3
      1359354.96      6875388.01      1359758.32      6875241.34
      1360305.00      6874438.00
#Sta/Elev= 30
  4570.8 2201.22  4663.5 2196.55  4723.8 2194.09  4838.2 2189.23  4962.5 2183.58
  5057.4 2184.10  5064.5 2184.88  5195.0 2184.10  5201.1 2184.87  5266.8 2185.39
  5380.7 2188.24  5461.4 2188.42  5482.4 2188.04  5533.2 2183.12  5539.3 2179.61
  5546.1 2178.96  5546.4 2178.46  5550.1 2178.96  5560.4 2183.25  5590.1 2185.82
  5605.1 2189.03  5620.0 2187.34  5626.0 2188.10  5633.0 2186.94  5641.0 2187.06
  5655.9 2188.42  5662.0 2190.21  5682.9 2191.25  5921.3 2198.32  5971.7 2199.22
#Mann=7,-1,0
  4570.8   0.035       0  4663.5    0.07       0  4723.8   0.035       0
  4838.2    0.07       0  5546.1    0.07       0  5550.1    0.07       0
  5921.3   0.035       0
Bank Sta=5546.1,5550.1
Exp/Cntr=0.3,0.1

Type RM Length L Ch R = 1,1977,984,984,984
BEGIN DESCRIPTION:
Sweetwater Creek Trib 27 T1 2.0
END DESCRIPTION:
XS GIS Cut Line= 3
      1359305.03      6875787.99      1360124.84      6875558.59
      1360305.00      6874537.97
#Sta/Elev= 30
  4148.7 2195.13  4303.7 2193.57  4678.3 2187.76  4758.6 2186.12  4782.1 2184.37
  4792.5 2184.48  4803.1 2186.96  4813.3 2185.25  4832.0 2184.12  4871.3 2183.90
  4912.4 2182.18  4950.0 2181.56  4958.6 2180.40  4989.8 2179.41  5030.1 2180.36
  5051.4 2181.22  5146.3 2180.62  5254.5 2183.03  5366.2 2183.00  5432.3 2178.83
  5435.3 2177.51  5435.5 2177.01  5439.4 2177.51  5447.4 2178.68  5491.5 2180.14
  5550.7 2185.05  5599.7 2185.24  5670.8 2188.42  5884.1 2193.07  6036.4 2197.79
#Mann=6,-1,0
  4148.7   0.035       0  4303.7    0.07       0  4912.4   0.035       0
  5030.1    0.07       0  5435.3   0.035       0  5439.4    0.07       0
Bank Sta=5435.3,5439.4
Exp/Cntr=0.3,0.1

Type RM Length L Ch R = 1,993,495,495,495
BEGIN DESCRIPTION:
Sweetwater Creek Trib 27 T1 1.0
END DESCRIPTION:
XS GIS Cut Line= 3
      1359904.97      6875838.00      1360691.16      6875824.87
      1360854.99      6875638.02
#Sta/Elev= 30
  4213.7 2186.55  4217.8 2186.49  4253.7 2185.23  4333.7 2184.40  4413.8 2182.43
  4516.0 2181.21  4563.8 2179.68  4645.2 2178.46  4903.8 2176.00  4920.9 2174.75
  4929.2 2174.27  4973.8 2171.88  4983.8 2172.50  4996.9 2169.42  4997.3 2168.92
  5001.5 2168.92  5001.9 2169.42  5014.6 2171.93  5043.1 2172.71  5049.7 2174.22
  5057.3 2174.02  5071.5 2175.05  5078.2 2176.29  5092.4 2177.50  5106.6 2178.27
  5114.2 2177.82  5120.9 2178.97  5163.6 2180.89  5198.7 2183.70  5248.5 2186.29
#Mann=7,-1,0
  4213.7    0.07       0  4217.8   0.035       0  4645.2    0.07       0
  4920.9    0.16       0  4929.2    0.07       0  4996.9    0.07       0
  5001.9    0.07       0
Bank Sta=4996.9,5001.9
Exp/Cntr=0.3,0.1

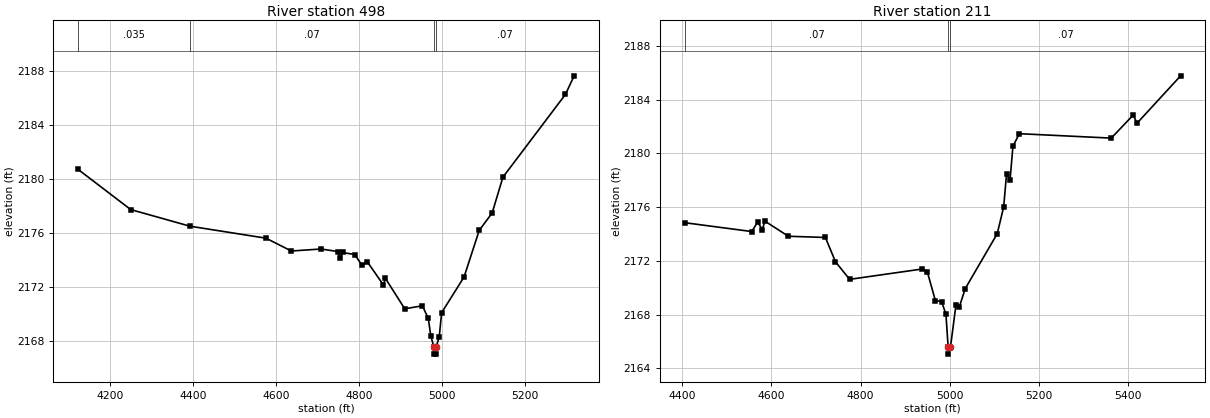
Type RM Length L Ch R = 1,498,287,287,287
BEGIN DESCRIPTION:
Sweetwater Creek Trib 27 T1 0.1
END DESCRIPTION:
XS GIS Cut Line= 3
      1360140.75      6875922.19      1361001.14      6876089.42
      1361105.00      6875788.01
#Sta/Elev= 30
  4123.5 2180.68  4250.1 2177.71  4392.6 2176.48  4576.1 2175.59  4637.2 2174.64
  4708.9 2174.79  4749.2 2174.60  4755.5 2174.09  4760.6 2174.53  4790.0 2174.38
  4807.2 2173.59  4820.6 2173.83  4858.9 2172.13  4864.0 2172.61  4910.5 2170.36
  4953.0 2170.58  4967.3 2169.64  4973.4 2168.33  4981.0 2167.50  4981.4 2167.00
  4985.7 2167.00  4986.1 2167.50  4993.7 2168.30  4999.4 2170.07  5053.5 2172.72
  5090.0 2176.17  5121.2 2177.46  5147.1 2180.11  5297.7 2186.24  5318.8 2187.62
#Mann=4,-1,0
  4123.5   0.035       0  4392.6    0.07       0  4981.0    0.07       0
  4986.1    0.07       0
Bank Sta=4981,4986.1
Exp/Cntr=0.3,0.1

Type RM Length L Ch R = 1,211,0,0,0
BEGIN DESCRIPTION:
Sweetwater Creek Trib 27 T1 4498
END DESCRIPTION:
XS GIS Cut Line= 3
      1360524.17      6876123.13      1361071.98      6876354.61
      1361398.04      6875952.23
#Sta/Elev= 30
  4405.3 2174.84  4555.9 2174.18  4569.0 2174.89  4579.6 2174.32  4585.1 2174.96
  4637.9 2173.83  4721.0 2173.74  4743.6 2171.93  4775.3 2170.62  4938.1 2171.39
  4949.5 2171.20  4967.7 2169.04  4981.6 2168.97  4991.4 2168.03  4996.4 2165.55
  4996.8 2165.05  5001.5 2165.55  5013.8 2168.69  5021.4 2168.56  5034.7 2169.93
  5106.5 2174.02  5120.9 2176.01  5127.4 2178.47  5135.3 2178.04  5141.7 2180.53
  5156.1 2181.47  5362.3 2181.14  5411.9 2182.87  5419.8 2182.24  5517.9 2185.78
#Mann=3,-1,0
  4405.3    0.07       0  4996.4    0.07       0  5001.5    0.07       0
Bank Sta=4996.4,5001.5
Exp/Cntr=0.3,0.1

Chan Stop Cuts=-1