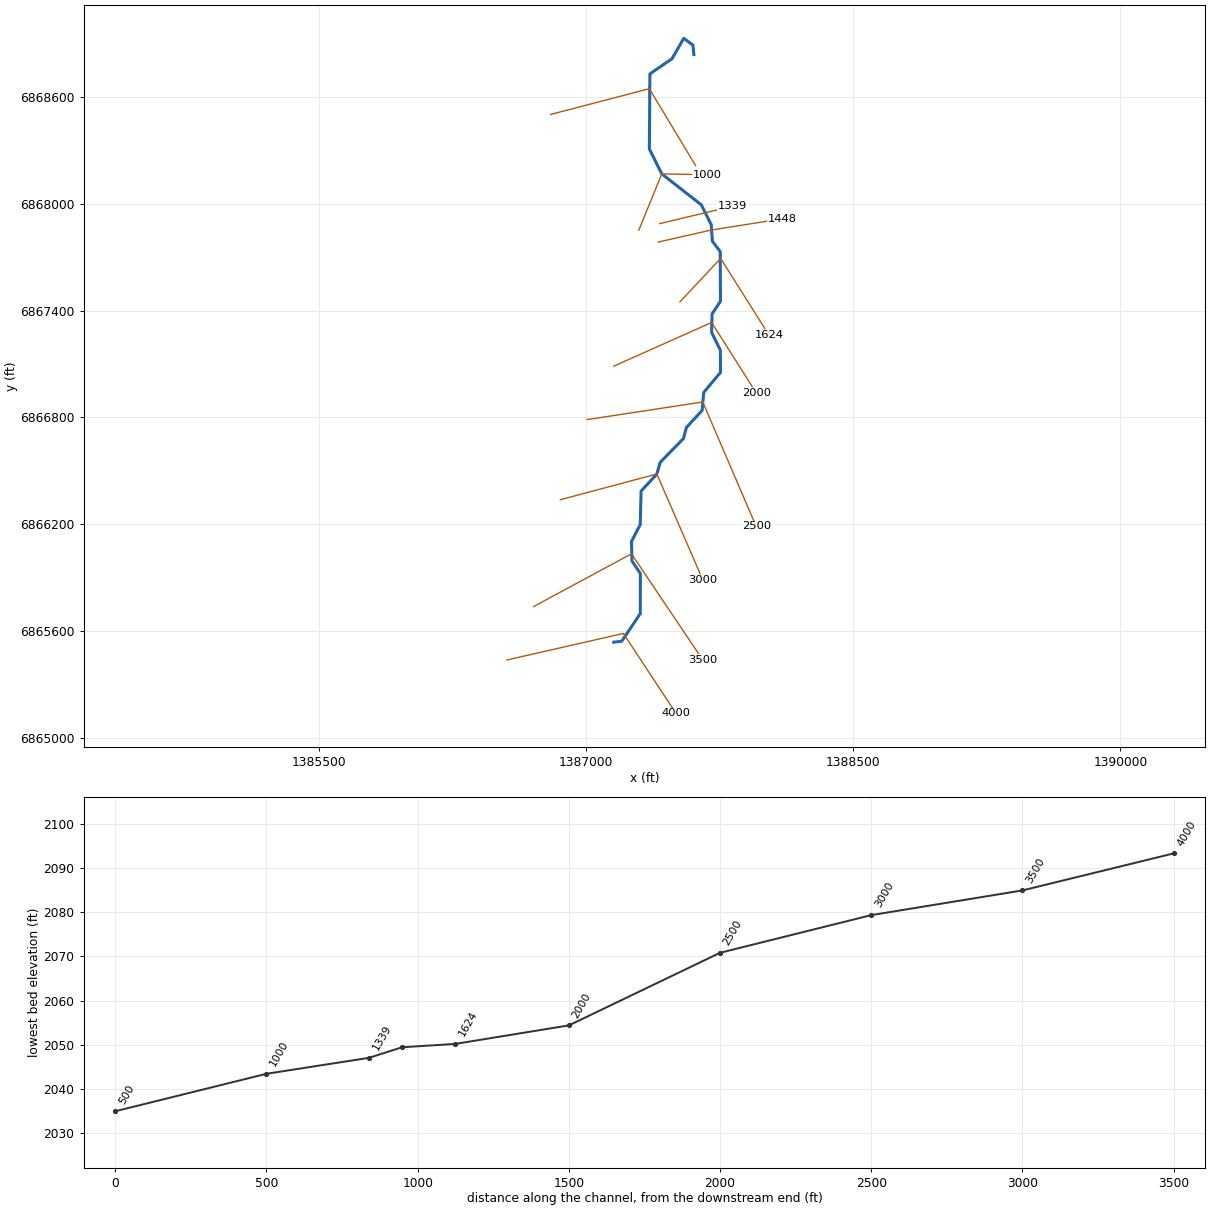
--- Sweetwater Creek Trib 27 T10.prj (project) ---

Proj Title=Sweetwater Creek Trib 27 T10 Base Level Engineering
Current Plan=p01
Default Exp/Contr=0.3,0.1
English Units
Geom File=g01
Flow File=f01
Plan File=p01
BEGIN DESCRIPTION:
Sweetwater Creek Trib 27 T10
END DESCRIPTION:

--- Sweetwater Creek Trib 27 T10.p01 (plan) ---

Plan Title=Multiple Run
Short Identifier=Multiple
Geom File=g01
Flow File=f01
Subcritical Flow
K Sum by GR= 0
Std Step Tol= 0.01
Critical Tol= 0.01
Num of Std Step Trials= 20
Max Error Tol= 0.3
Flow Tol Ratio= 0.001
Split Flow NTrial= 30
Split Flow Tol= 0.02
Split Flow Ratio= 0.02
Log Output Level= 0
Friction Slope Method= 1
Unsteady Friction Slope Method= 2
Unsteady Bridges Friction Slope Method= 1
Parabolic Critical Depth
Global Vel Dist=  1 , 1 , 1
Global Log Level= 0
CheckData=True
Encroach Param= -1, 0, 0, 0
BEGIN DESCRIPTION:
Multiple Run
END DESCRIPTION:

--- Sweetwater Creek Trib 27 T10.f01 (steady flow) ---

Flow Title=Multiple
Number of Profiles=7
Profile Names=10-year,25-year,50-year,1pct_min,100-year,1pct_plu,500-year
River Rch & RM= Sweetwater Creek,Reach-1,4000
     133     182     221     134     268     535     398
Boundary for River Rch & Prof#=Sweetwater Creek,Reach-1,1
Up Type=0
Dn Type=3
Dn Slope=0.005
Boundary for River Rch & Prof#=Sweetwater Creek,Reach-1,2
Up Type=0
Dn Type=3
Dn Slope=0.005
Boundary for River Rch & Prof#=Sweetwater Creek,Reach-1,3
Up Type=0
Dn Type=3
Dn Slope=0.005
Boundary for River Rch & Prof#=Sweetwater Creek,Reach-1,4
Up Type=0
Dn Type=3
Dn Slope=0.005
Boundary for River Rch & Prof#=Sweetwater Creek,Reach-1,5
Up Type=0
Dn Type=3
Dn Slope=0.005
Boundary for River Rch & Prof#=Sweetwater Creek,Reach-1,6
Up Type=0
Dn Type=3
Dn Slope=0.005
Boundary for River Rch & Prof#=Sweetwater Creek,Reach-1,7
Up Type=0
Dn Type=3
Dn Slope=0.005

--- Sweetwater Creek Trib 27 T10.g01 (geometry) ---

Geom Title=Existing Conditions

River Reach=Sweetwater Creek,Reach-1
Reach XY= 30
      1387155.00      6865538.00      1387199.68      6865542.92
      1387303.95      6865698.44      1387304.48      6865922.78
      1387257.25      6865993.94      1387254.53      6866103.16
      1387303.78      6866198.51      1387308.55      6866386.53
      1387396.82      6866481.96      1387415.78      6866547.68
      1387546.84      6866681.95      1387563.18      6866744.04
      1387651.37      6866839.50      1387660.54      6866940.42
      1387754.63      6867053.17      1387753.79      6867177.49
      1387704.50      6867277.83      1387707.25      6867382.06
      1387754.48      6867453.22      1387752.74      6867732.06
      1387708.86      6867789.60      1387702.67      6867882.03
      1387646.87      6867994.07      1387424.77      6868167.87
      1387355.06      6868308.03      1387358.07      6868729.70
      1387482.00      6868814.50      1387548.15      6868929.31
      1387599.67      6868891.38      1387605.00      6868838.00

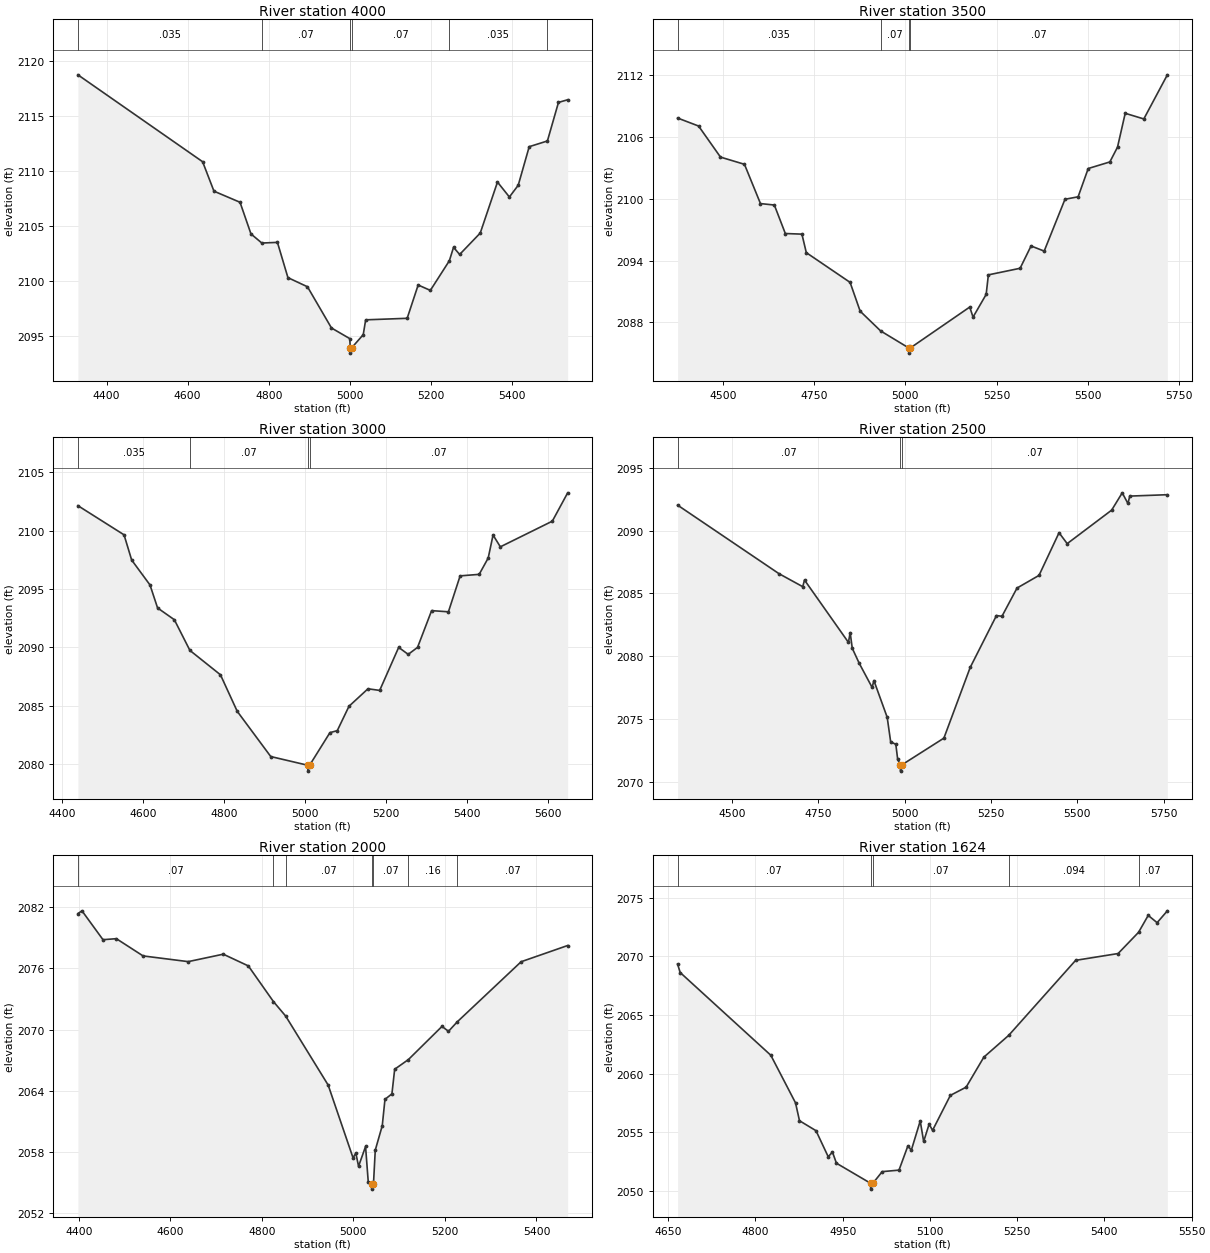
Type RM Length L Ch R = 1,4000,500,500,500
BEGIN DESCRIPTION:
Sweetwater Creek Trib 27 T10 7.0
END DESCRIPTION:
XS GIS Cut Line= 3
      1386555.00      6865438.00      1387209.09      6865586.78
      1387505.03      6865137.96
#Sta/Elev= 30
  4329.2 2118.73  4636.9 2110.82  4664.9 2108.14  4729.2 2107.13  4756.2 2104.25
  4783.0 2103.42  4821.5 2103.48  4847.4 2100.27  4895.6 2099.44  4954.8 2095.69
  5000.0 2094.72  5001.1 2093.90  5001.3 2093.40  5005.1 2093.90  5033.2 2095.08
  5039.2 2096.43  5141.6 2096.57  5168.7 2099.60  5198.8 2099.11  5245.7 2101.81
  5256.0 2103.03  5271.1 2102.38  5321.9 2104.33  5364.4 2108.97  5393.8 2107.61
  5415.6 2108.68  5442.7 2112.19  5487.6 2112.71  5514.9 2116.22  5537.6 2116.46
#Mann=6,-1,0
  4329.2   0.035       0  4783.0    0.07       0  5001.1    0.07       0
  5005.1    0.07       0  5245.7   0.035       0  5487.6   0.063       0
Bank Sta=5001.1,5005.1
Exp/Cntr=0.3,0.1

Type RM Length L Ch R = 1,3500,500,500,500
BEGIN DESCRIPTION:
Sweetwater Creek Trib 27 T10 6.0
END DESCRIPTION:
XS GIS Cut Line= 3
      1386705.03      6865738.02      1387254.52      6866034.14
      1387655.02      6865437.97
#Sta/Elev= 30
  4375.8 2107.86  4433.4 2107.08  4493.4 2104.06  4559.1 2103.36  4603.0 2099.54
  4641.0 2099.40  4671.1 2096.63  4716.6 2096.57  4728.6 2094.77  4848.6 2091.88
  4876.2 2089.08  4932.3 2087.16  5009.6 2085.50  5009.9 2085.00  5013.6 2085.50
  5176.6 2089.48  5185.6 2088.50  5221.6 2090.71  5227.6 2092.61  5314.6 2093.25
  5344.6 2095.42  5380.6 2094.92  5437.6 2099.96  5473.6 2100.20  5501.3 2102.95
  5560.6 2103.59  5581.6 2105.03  5602.7 2108.32  5653.7 2107.77  5718.2 2112.06
#Mann=4,-1,0
  4375.8   0.035       0  4932.3    0.07       0  5009.6    0.07       0
  5013.6    0.07       0
Bank Sta=5009.6,5013.6
Exp/Cntr=0.3,0.1

Type RM Length L Ch R = 1,3000,500,500,500
BEGIN DESCRIPTION:
Sweetwater Creek Trib 27 T10 5.0
END DESCRIPTION:
XS GIS Cut Line= 3
      1386854.96      6866337.99      1387397.14      6866482.48
      1387655.00      6865888.00
#Sta/Elev= 30
  4438.9 2102.15  4552.8 2099.65  4571.6 2097.49  4616.9 2095.35  4635.6 2093.38
  4677.0 2092.37  4715.4 2089.74  4790.8 2087.65  4832.2 2084.52  4915.0 2080.64
  5006.8 2079.89  5007.0 2079.39  5010.8 2079.89  5061.1 2082.69  5079.2 2082.86
  5108.1 2084.95  5155.0 2086.45  5183.9 2086.31  5230.8 2090.00  5254.3 2089.40
  5277.4 2090.00  5312.1 2093.15  5353.6 2093.05  5382.5 2096.13  5429.5 2096.26
  5451.8 2097.66  5463.8 2099.63  5481.8 2098.62  5610.1 2100.82  5648.0 2103.25
#Mann=4,-1,0
  4438.9   0.035       0  4715.4    0.07       0  5006.8    0.07       0
  5010.8    0.07       0
Bank Sta=5006.8,5010.8
Exp/Cntr=0.3,0.1

Type RM Length L Ch R = 1,2500,500,500,500
BEGIN DESCRIPTION:
Sweetwater Creek Trib 27 T10 4.0
END DESCRIPTION:
XS GIS Cut Line= 3
      1387004.98      6866788.00      1387655.00      6866886.88
      1387955.02      6866187.95
#Sta/Elev= 30
  4342.5 2092.04  4635.9 2086.58  4704.9 2085.54  4710.0 2086.07  4837.2 2081.10
  4842.2 2081.88  4848.3 2080.63  4868.5 2079.43  4905.8 2077.51  4910.9 2078.06
  4949.4 2075.13  4959.5 2073.17  4974.4 2072.98  4979.8 2071.77  4987.9 2071.34
  4988.1 2070.84  4991.9 2071.34  5113.6 2073.47  5189.7 2079.10  5265.8 2083.24
  5281.7 2083.18  5325.3 2085.43  5389.0 2086.44  5447.0 2089.84  5470.6 2088.97
  5599.3 2091.64  5630.0 2093.02  5646.4 2092.17  5651.8 2092.76  5760.6 2092.87
#Mann=3,-1,0
  4342.5    0.07       0  4987.9    0.07       0  4991.9    0.07       0
Bank Sta=4987.9,4991.9
Exp/Cntr=0.3,0.1

Type RM Length L Ch R = 1,2000,376,376,376
BEGIN DESCRIPTION:
Sweetwater Creek Trib 27 T10 3.0
END DESCRIPTION:
XS GIS Cut Line= 3
      1387155.00      6867088.00      1387704.54      6867333.55
      1387955.01      6866937.98
#Sta/Elev= 30
  4398.1 2081.37  4407.0 2081.64  4452.9 2078.81  4482.1 2078.91  4540.5 2077.22
  4639.1 2076.66  4715.7 2077.39  4770.5 2076.24  4825.4 2072.74  4852.1 2071.32
  4944.9 2064.56  4999.3 2057.42  5005.4 2057.89  5011.3 2056.60  5026.6 2058.54
  5032.5 2055.06  5039.9 2054.86  5040.1 2054.36  5043.9 2054.86  5047.8 2058.18
  5063.1 2060.58  5069.0 2063.16  5084.2 2063.70  5090.2 2066.11  5120.2 2067.06
  5193.6 2070.31  5207.8 2069.83  5227.0 2070.76  5366.5 2076.65  5468.2 2078.24
#Mann=7,-1,0
  4398.1    0.07       0  4825.4    0.16       0  4852.1    0.07       0
  5039.9    0.07       0  5043.9    0.07       0  5120.2    0.16       0
  5227.0    0.07       0
Bank Sta=5039.9,5043.9
Exp/Cntr=0.3,0.1

Type RM Length L Ch R = 1,1624,176,176,176
BEGIN DESCRIPTION:
Sweetwater Creek Trib 27 T10 3997
END DESCRIPTION:
XS GIS Cut Line= 3
      1387527.02      6867449.63      1387755.44      6867693.18
      1388026.33      6867263.20
#Sta/Elev= 30
  4666.1 2069.33  4670.6 2068.61  4826.4 2061.56  4868.9 2057.50  4875.7 2055.98
  4904.1 2055.13  4925.1 2052.91  4932.4 2053.31  4939.2 2052.36  4997.9 2050.65
  4998.1 2050.15  5001.9 2050.65  5017.9 2051.64  5046.8 2051.77  5062.1 2053.84
  5068.0 2053.47  5083.3 2055.96  5089.2 2054.21  5098.6 2055.69  5104.5 2055.16
  5135.1 2058.14  5162.2 2058.84  5192.7 2061.40  5235.5 2063.26  5350.5 2069.65
  5423.5 2070.23  5458.7 2072.04  5475.3 2073.48  5490.6 2072.86  5508.2 2073.87
#Mann=5,-1,0
  4666.1    0.07       0  4997.9    0.07       0  5001.9    0.07       0
  5235.5   0.094       0  5458.7    0.07       0
Bank Sta=4997.9,5001.9
Exp/Cntr=0.3,0.1

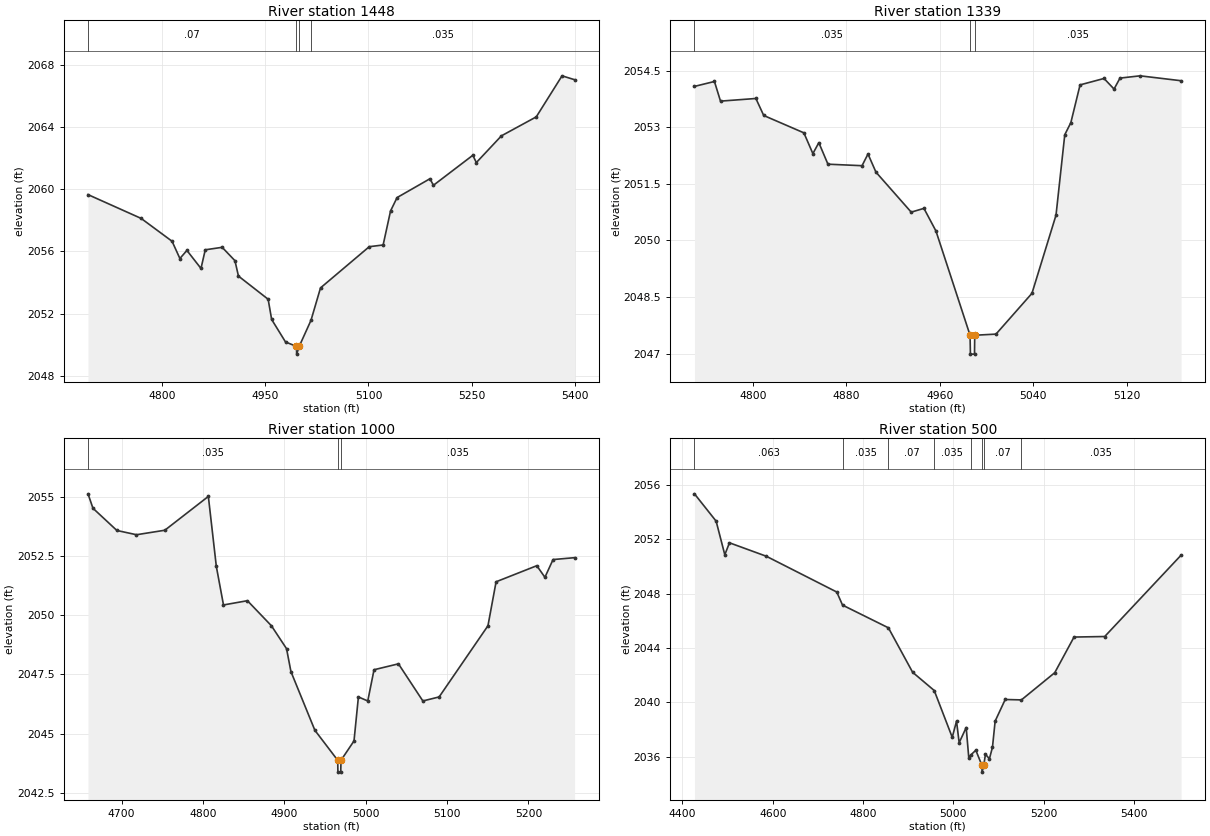
Type RM Length L Ch R = 1,1448,109,109,109
BEGIN DESCRIPTION:
Sweetwater Creek Trib 27 T10 2.0
END DESCRIPTION:
XS GIS Cut Line= 3
      1387404.63      6867785.17      1387705.16      6867853.06
      1388100.15      6867915.52
#Sta/Elev= 30
  4691.9 2059.65  4769.2 2058.12  4814.2 2056.65  4825.6 2055.54  4835.8 2056.06
  4856.3 2054.90  4862.5 2056.10  4887.1 2056.26  4905.7 2055.40  4910.8 2054.41
  4954.0 2052.92  4959.1 2051.62  4979.3 2050.17  4995.2 2049.89  4995.5 2049.39
  4999.2 2049.89  5016.3 2051.56  5030.2 2053.65  5101.1 2056.30  5121.3 2056.41
  5132.1 2058.60  5141.6 2059.46  5189.4 2060.67  5194.5 2060.25  5251.8 2062.18
  5256.9 2061.71  5293.4 2063.43  5344.1 2064.65  5381.6 2067.29  5399.9 2067.04
#Mann=4,-1,0
  4691.9    0.07       0  4995.2    0.07       0  4999.2    0.07       0
  5016.3   0.035       0
Bank Sta=4995.2,4999.2
Exp/Cntr=0.3,0.1

Type RM Length L Ch R = 1,1339,339,339,339
BEGIN DESCRIPTION:
Sweetwater Creek Trib 27 T10 3996
END DESCRIPTION:
XS GIS Cut Line= 2
      1387413.84      6867888.90      1387819.18      6867985.54
#Sta/Elev= 30
  4749.9 2054.08  4767.0 2054.21  4772.2 2053.69  4802.5 2053.76  4809.2 2053.31
  4843.6 2052.85  4851.3 2052.30  4856.4 2052.59  4864.2 2052.02  4893.4 2051.98
  4898.5 2052.29  4905.3 2051.81  4935.5 2050.75  4946.4 2050.85  4956.7 2050.25
  4985.9 2047.49  4986.2 2046.99  4989.7 2046.99  4989.9 2047.49  5008.1 2047.52
  5038.9 2048.60  5059.5 2050.67  5067.0 2052.80  5072.2 2053.12  5080.1 2054.12
  5100.6 2054.29  5109.2 2054.01  5114.3 2054.30  5131.5 2054.36  5166.6 2054.23
#Mann=3,-1,0
  4749.9   0.035       0  4985.9   0.035       0  4989.9   0.035       0
Bank Sta=4985.9,4989.9
Exp/Cntr=0.3,0.1

Type RM Length L Ch R = 1,1000,500,500,500
BEGIN DESCRIPTION:
Sweetwater Creek Trib 27 T10 1.0
END DESCRIPTION:
XS GIS Cut Line= 3
      1387295.77      6867852.03      1387424.71      6868167.93
      1387681.47      6868163.48
#Sta/Elev= 30
  4658.8 2055.14  4664.9 2054.53  4694.3 2053.59  4718.4 2053.41  4753.2 2053.60
  4806.7 2055.03  4816.5 2052.07  4825.3 2050.44  4854.7 2050.62  4884.2 2049.56
  4902.8 2048.59  4908.2 2047.62  4937.6 2045.14  4965.7 2043.87  4965.9 2043.37
  4969.4 2043.37  4969.7 2043.87  4985.7 2044.69  4991.1 2046.55  5002.6 2046.38
  5010.3 2047.70  5040.3 2047.95  5070.3 2046.38  5090.3 2046.55  5150.3 2049.56
  5160.3 2051.42  5210.3 2052.10  5220.3 2051.61  5230.3 2052.36  5256.8 2052.44
#Mann=3,-1,0
  4658.8   0.035       0  4965.7   0.035       0  4969.7   0.035       0
Bank Sta=4965.7,4969.7
Exp/Cntr=0.3,0.1

Type RM Length L Ch R = 1,500,0,0,0
BEGIN DESCRIPTION:
Sweetwater Creek Trib 27 T10 3893
END DESCRIPTION:
XS GIS Cut Line= 3
      1386799.96      6868501.82      1387354.83      6868646.39
      1387614.94      6868214.34
#Sta/Elev= 30
  4426.6 2055.33  4474.6 2053.32  4493.8 2050.85  4504.1 2051.73  4585.8 2050.74
  4741.8 2048.11  4754.5 2047.15  4856.1 2045.48  4909.8 2042.21  4957.6 2040.87
  4997.5 2037.43  5007.0 2038.62  5012.8 2037.03  5028.4 2038.15  5034.2 2035.89
  5038.2 2036.12  5049.7 2036.48  5063.2 2035.37  5063.5 2034.87  5067.2 2035.37
  5071.1 2036.18  5079.8 2035.85  5086.6 2036.70  5092.5 2038.62  5114.8 2040.21
  5150.7 2040.18  5224.5 2042.18  5267.2 2044.80  5335.2 2044.84  5504.3 2050.82
#Mann=8,-1,0
  4426.6   0.063       0  4754.5   0.035       0  4856.1    0.07       0
  4957.6   0.035       0  5038.2    0.07       0  5063.2   0.035       0
  5067.2    0.07       0  5150.7   0.035       0
Bank Sta=5063.2,5067.2
Exp/Cntr=0.3,0.1

Chan Stop Cuts=-1