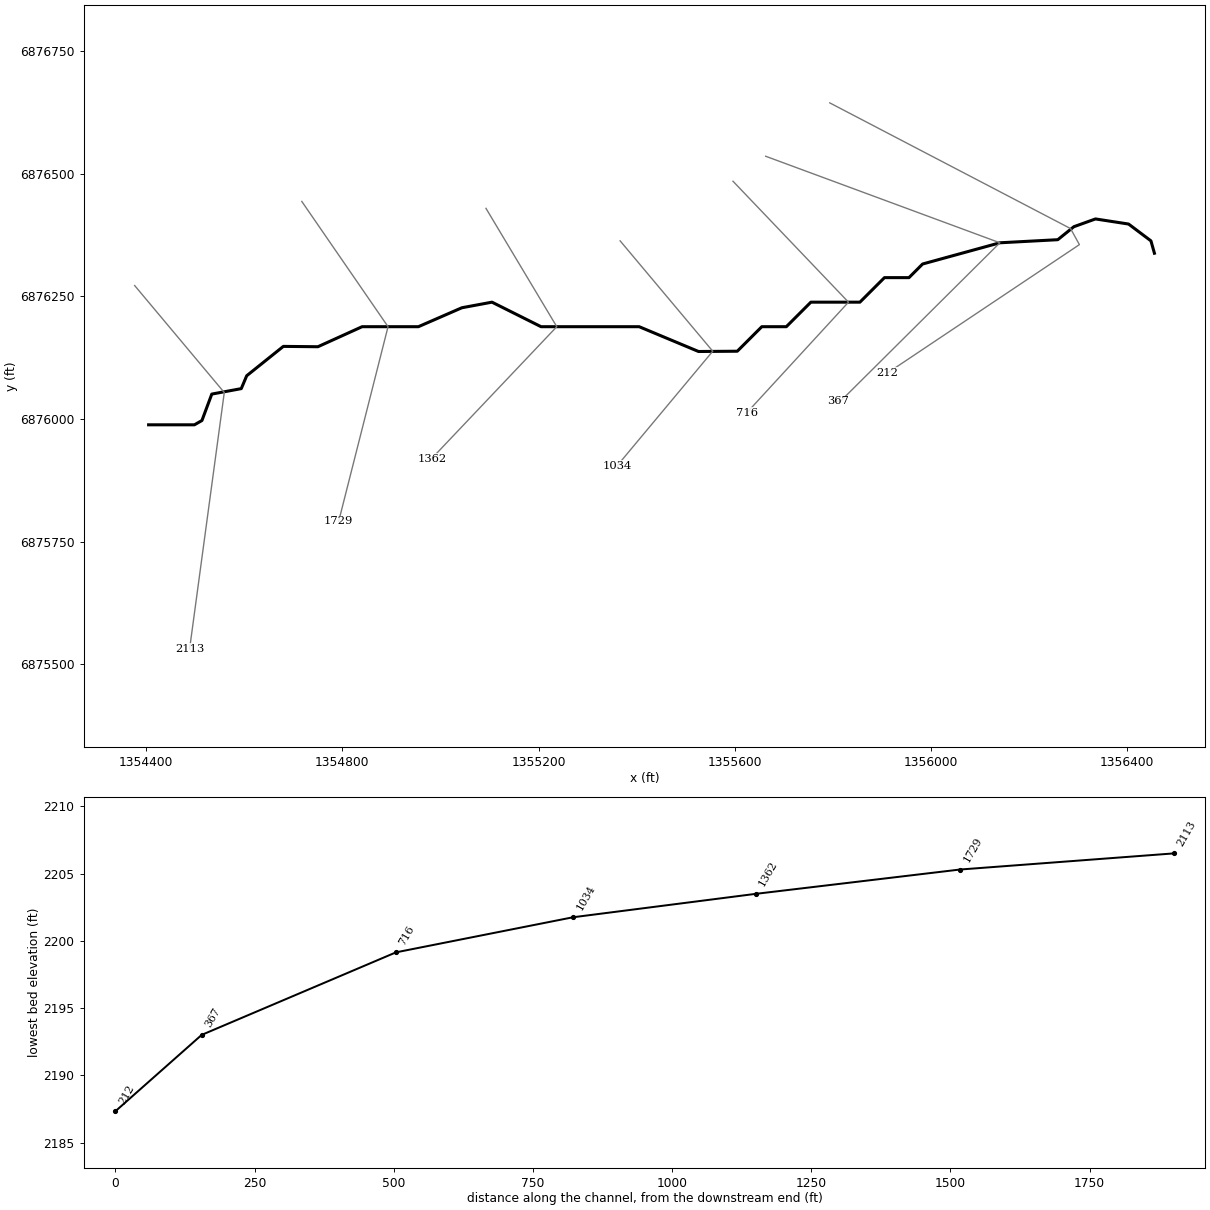
--- Sweetwater Creek Trib 27 T101.prj (project) ---

Proj Title=Sweetwater Creek Trib 27 T101 Base Level Engineering
Current Plan=p01
Default Exp/Contr=0.3,0.1
English Units
Geom File=g01
Flow File=f01
Plan File=p01
Y Axis Title=Elevation
X Axis Title(PF)=Main Channel Distance
X Axis Title(XS)=Station
BEGIN DESCRIPTION:
Sweetwater Creek Trib 27 T101
END DESCRIPTION:
DSS Export Rating Curves= 0
DSS Export Rating Curve Sorted= 0
DSS Export Volume Flow Curves= 0
DXF OffsetX= 0
DXF OffsetY= 0
DXF ScaleX= 1
DXF ScaleY= 10

--- Sweetwater Creek Trib 27 T101.p01 (plan) ---

Plan Title=Multiple Run
Short Identifier=Multiple
Geom File=g01
Flow File=f01
Subcritical Flow
K Sum by GR= 0
Std Step Tol= 0.01
Critical Tol= 0.01
Num of Std Step Trials= 20
Max Error Tol= 0.3
Flow Tol Ratio= 0.001
Split Flow NTrial= 30
Split Flow Tol= 0.02
Split Flow Ratio= 0.02
Log Output Level= 0
Friction Slope Method= 1
Unsteady Friction Slope Method= 2
Unsteady Bridges Friction Slope Method= 1
Parabolic Critical Depth
Global Vel Dist=  1 , 1 , 1
Global Log Level= 0
CheckData=True
Encroach Param= -1, 0, 0, 0
BEGIN DESCRIPTION:
Multiple Run
END DESCRIPTION:

--- Sweetwater Creek Trib 27 T101.f01 (steady flow) ---

Flow Title=Multiple
Program Version=4.10
Number of Profiles= 7
Profile Names=10-year,25-year,50-year,1pct_min,100-year,1pct_plu,500-year
River Rch & RM=Sweetwater Creek,Reach-1         ,2113
     479     711     914     584    1166    2326    1923
Boundary for River Rch & Prof#=Sweetwater Creek,Reach-1         , 1
Up Type= 0
Dn Type= 3
Dn Slope=0.023
Boundary for River Rch & Prof#=Sweetwater Creek,Reach-1         , 2
Up Type= 0
Dn Type= 3
Dn Slope=0.023
Boundary for River Rch & Prof#=Sweetwater Creek,Reach-1         , 3
Up Type= 0
Dn Type= 3
Dn Slope=0.023
Boundary for River Rch & Prof#=Sweetwater Creek,Reach-1         , 4
Up Type= 0
Dn Type= 3
Dn Slope=0.023
Boundary for River Rch & Prof#=Sweetwater Creek,Reach-1         , 5
Up Type= 0
Dn Type= 3
Dn Slope=0.023
Boundary for River Rch & Prof#=Sweetwater Creek,Reach-1         , 6
Up Type= 0
Dn Type= 3
Dn Slope=0.023
Boundary for River Rch & Prof#=Sweetwater Creek,Reach-1         , 7
Up Type= 0
Dn Type= 3
Dn Slope=0.023
DSS Import GetInterval= 0
DSS Import GetPeak= 0
DSS Import FillOption= 0

--- Sweetwater Creek Trib 27 T101.g01 (geometry) ---

Geom Title=Existing Conditions
Program Version=4.10

River Reach=Sweetwater Creek,Reach-1
Reach XY= 30
        1354405.        6875988.      1354498.42        6875988.
      1354513.75      6875996.75      1354533.83      6876050.63
       1354593.9      6876061.74        1354605.        6876088.
      1354679.67      6876147.85      1354750.15      6876147.16
      1354840.26        6876188.        1354955.        6876188.
      1355043.61      6876226.61        1355105.        6876238.
        1355205.        6876188.        1355405.        6876188.
      1355526.02      6876137.44        1355605.        6876138.
        1355655.        6876188.        1355705.        6876188.
        1355755.        6876238.        1355855.        6876238.
        1355905.        6876288.        1355955.        6876288.
      1355982.79      6876315.79      1356140.28      6876359.04
      1356258.33      6876365.34       1356291.1      6876391.81
      1356335.16      6876407.65      1356402.65      6876397.24
      1356448.22      6876362.95      1356455.33      6876337.73

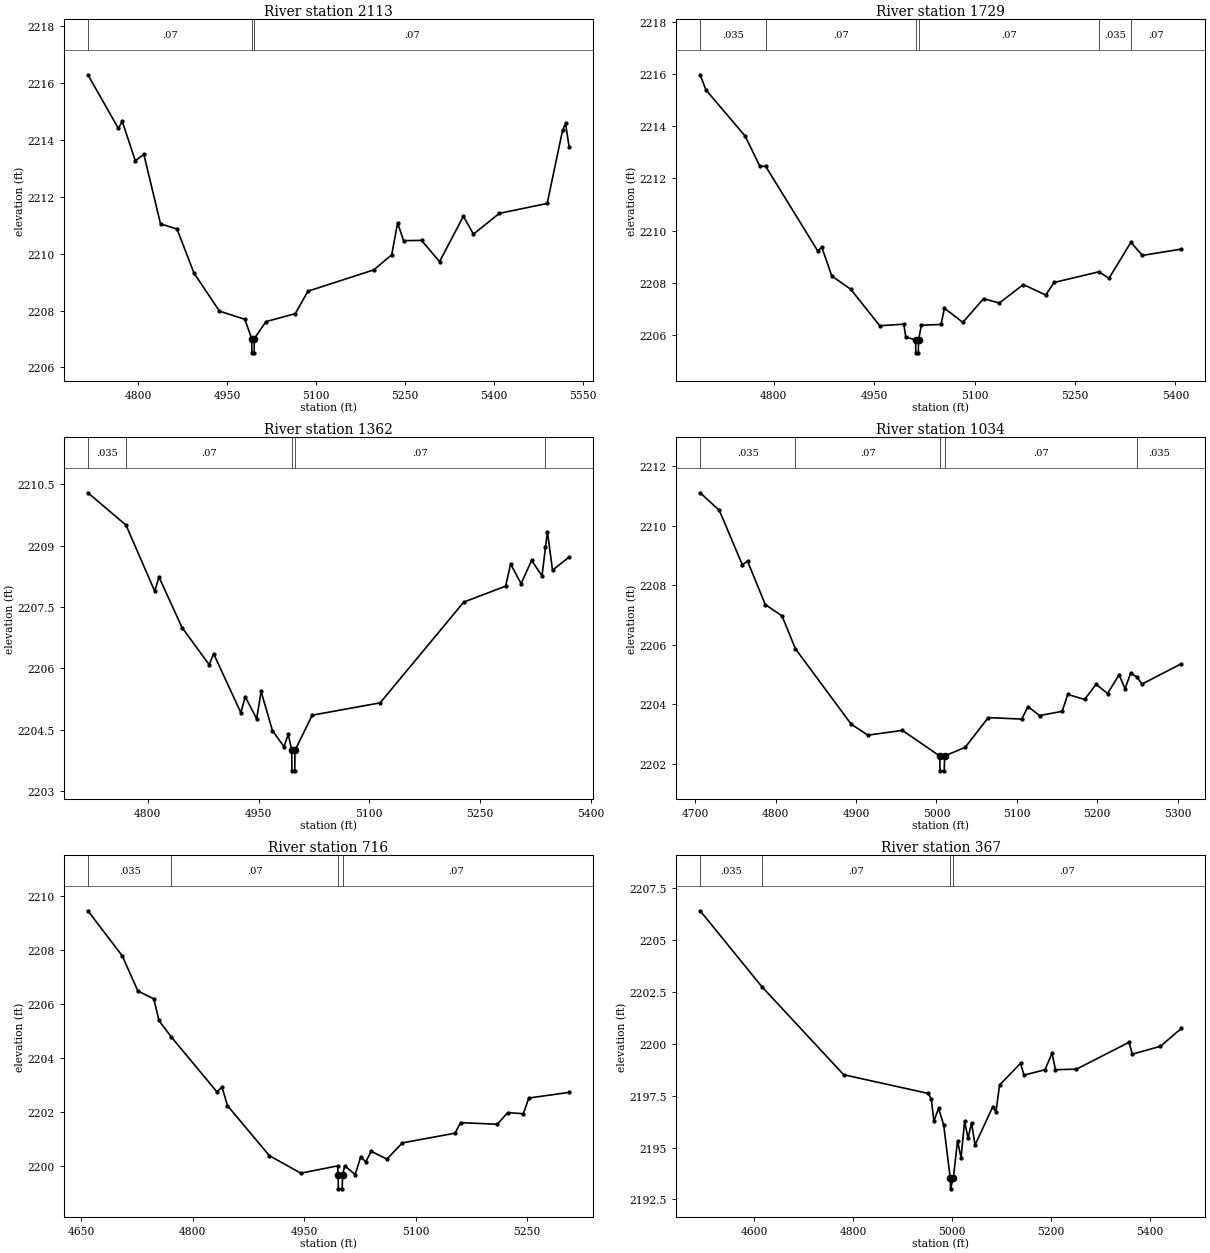
Type RM Length L Ch R = 1 ,2113    ,384,384,384
BEGIN DESCRIPTION:
Sweetwater Creek Trib 27 T101 4411
END DESCRIPTION:
XS GIS Cut Line= 3
      1354376.59      6876271.89      1354559.28      6876053.79
       1354488.6      6875531.35
#Sta/Elev= 30
  4715.5  2216.3  4766.9 2214.41  4773.4 2214.66  4795.5 2213.27  4809.8  2213.5
    4838 2211.05  4865.8 2210.87  4894.4 2209.32  4937.3 2207.98  4980.2 2207.69
  4991.8 2207.01  4992.1 2206.51  4995.9 2206.51  4996.2 2207.01  5015.9 2207.61
  5065.3 2207.89  5086.6 2208.68  5197.6 2209.43  5227.9 2209.96  5237.9 2211.08
    5248 2210.46  5278.3 2210.47  5308.6 2209.72  5348.9 2211.32  5365.8 2210.69
  5409.5 2211.42  5490.2 2211.77  5516.1 2214.34  5521.2 2214.59  5527.2 2213.76
#Mann= 3 ,-1 , 0
  4715.5     .07       0  4991.8     .07       0  4996.2     .07       0
Bank Sta=4991.8,4996.2
XS Rating Curve= 0 ,0
Exp/Cntr=0.3,0.1

Type RM Length L Ch R = 1 ,1729    ,367,367,367
BEGIN DESCRIPTION:
Sweetwater Creek Trib 27 T101 4410
END DESCRIPTION:
XS GIS Cut Line= 3
       1354717.3      6876443.33      1354893.11        6876188.
      1354792.57      6875791.55
#Sta/Elev= 30
    4690 2215.98  4698.6  2215.4  4757.2 2213.63  4779.2 2212.47  4787.8 2212.47
  4865.7 2209.22  4871.8 2209.36  4886.7 2208.26    4915 2207.75  4958.4 2206.35
  4994.2 2206.41  4997.3 2205.91  5011.9 2205.81  5012.2 2205.31    5016 2205.31
  5016.3 2205.81  5020.6 2206.37  5049.9  2206.4    5055 2207.02  5082.5 2206.48
  5113.5 2207.39    5137 2207.22  5172.8 2207.93  5206.3 2207.53  5218.9 2208.01
    5286 2208.42  5300.9 2208.17  5333.6 2209.55  5350.8 2209.05    5409 2209.29
#Mann= 6 ,-1 , 0
    4690    .035       0  4787.8     .07       0  5011.9     .07       0
  5016.3     .07       0    5286    .035       0  5333.6     .07       0
Bank Sta=5011.9,5016.3
XS Rating Curve= 0 ,0
Exp/Cntr=0.3,0.1

Type RM Length L Ch R = 1 ,1362    ,328,328,328
BEGIN DESCRIPTION:
Sweetwater Creek Trib 27 T101 4409
END DESCRIPTION:
XS GIS Cut Line= 3
      1355092.74      6876429.22      1355237.07        6876188.
      1354982.08      6875919.21
#Sta/Elev= 30
  4718.9 2210.29  4770.5  2209.5  4809.3 2207.89  4815.2 2208.23  4846.3    2207
  4883.2 2206.09  4889.1 2206.36    4926 2204.92  4931.9 2205.31  4947.4 2204.77
  4953.4 2205.44  4968.8 2204.48  4984.4 2204.09  4990.2 2204.39  4994.9    2204
  4995.2  2203.5    4999  2203.5  4999.3    2204  5022.7 2204.86  5114.6 2205.16
  5227.8 2207.62  5284.5 2208.01  5291.3 2208.55  5305.5 2208.07  5319.7 2208.64
  5333.8 2208.26  5338.5 2208.96  5341.1 2209.34    5348  2208.4  5370.5 2208.72
#Mann= 5 ,-1 , 0
  4718.9    .035       0  4770.5     .07       0  4994.9     .07       0
  4999.3     .07       0  5338.5    .035       0
Bank Sta=4994.9,4999.3
XS Rating Curve= 0 ,0
Exp/Cntr=0.3,0.1

Type RM Length L Ch R = 1 ,1034    ,318,318,318
BEGIN DESCRIPTION:
Sweetwater Creek Trib 27 T101 4408
END DESCRIPTION:
XS GIS Cut Line= 3
      1355366.21      6876362.98        1355555.        6876138.
      1355359.87      6875904.24
#Sta/Elev= 30
  4706.3 2211.11  4730.1 2210.52  4758.7 2208.69  4765.2 2208.81  4787.3 2207.35
  4808.1 2206.97  4824.6 2205.87    4894 2203.33  4914.8 2202.96  4957.7 2203.12
  5004.1 2202.26  5004.6 2201.76  5009.7 2201.76  5010.2 2202.26  5035.8 2202.55
  5064.4 2203.55  5106.1  2203.5  5113.9 2203.92  5128.2 2203.62  5156.3 2203.76
  5163.3 2204.33  5184.2 2204.16  5198.5 2204.67  5212.8 2204.36  5227.1 2204.99
  5234.5 2204.52  5241.4 2205.04  5248.9 2204.92  5255.7 2204.68  5304.5 2205.36
#Mann= 5 ,-1 , 0
  4706.3    .035       0  4824.6     .07       0  5004.1     .07       0
  5010.2     .07       0  5248.9    .035       0
Bank Sta=5004.1,5010.2
XS Rating Curve= 0 ,0
Exp/Cntr=0.3,0.1

Type RM Length L Ch R = 1 ,716     ,349,349,349
BEGIN DESCRIPTION:
Sweetwater Creek Trib 27 T101 4407
END DESCRIPTION:
XS GIS Cut Line= 3
      1355596.24      6876484.52      1355831.69        6876238.
       1355624.1      6876012.24
#Sta/Elev= 30
  4659.1 2209.44  4705.3 2207.77  4726.4 2206.47  4747.8 2206.18  4754.7 2205.38
  4771.3 2204.77  4832.7 2202.74  4839.6 2202.91  4846.9 2202.23  4903.2 2200.38
  4945.6 2199.73  4995.3    2200  4995.7 2199.65  4996.2 2199.15  5001.3 2199.15
  5001.8 2199.65  5004.6    2200  5018.8 2199.68  5026.2 2200.33    5033 2200.15
  5040.4 2200.54  5061.4 2200.25  5082.3 2200.85  5153.2 2201.21  5160.6  2201.6
    5210 2201.54  5224.1 2201.97  5245.1 2201.93  5252.5 2202.51  5306.7 2202.72
#Mann= 4 ,-1 , 0
  4659.1    .035       0  4771.3     .07       0  4995.7     .07       0
  5001.8     .07       0
Bank Sta=4995.7,5001.8
XS Rating Curve= 0 ,0
Exp/Cntr=0.3,0.1

Type RM Length L Ch R = 1 ,367     ,155,155,155
BEGIN DESCRIPTION:
Sweetwater Creek Trib 27 T101 4406
END DESCRIPTION:
XS GIS Cut Line= 4
      1355662.92      6876535.43      1356140.28      6876359.04
      1355815.42      6876036.12      1355809.47      6876036.12
#Sta/Elev= 30
  4491.1 2206.41  4615.6 2202.76  4781.2 2198.51  4951.7 2197.61  4958.4 2197.35
  4963.7 2196.27  4973.1 2196.89  4983.5 2196.09  4996.8 2193.51  4997.3 2193.01
  5002.9 2193.51  5011.5 2195.33  5018.6  2194.5  5025.7 2196.27  5032.8 2195.45
  5039.8 2196.19  5046.9 2195.12  5082.2 2196.94  5089.3 2196.73  5096.4 2198.01
  5138.8 2199.06  5145.9 2198.49  5188.3 2198.75  5202.5 2199.54  5209.5 2198.75
    5252 2198.78    5358 2200.07  5365.1  2199.5  5421.7 2199.88    5464 2200.74
#Mann= 4 ,-1 , 0
  4491.1    .035       0  4615.6     .07       0  4996.8     .07       0
  5002.9     .07       0
Bank Sta=4996.8,5002.9
XS Rating Curve= 0 ,0
Exp/Cntr=0.3,0.1

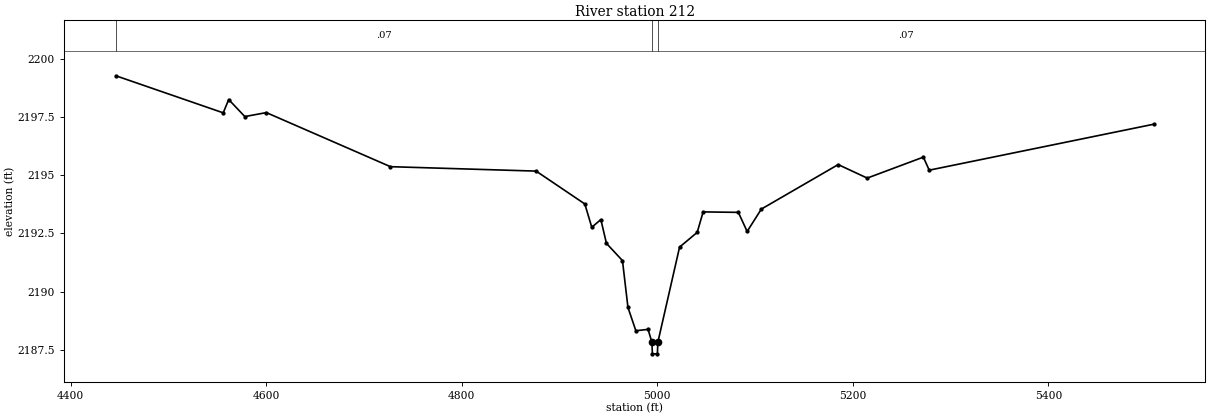
Type RM Length L Ch R = 1 ,212     ,0,0,0
BEGIN DESCRIPTION:
Sweetwater Creek Trib 27 T101 4507
END DESCRIPTION:
XS GIS Cut Line= 4
      1355793.53      6876644.23      1356284.38        6876388.
      1356302.39      6876355.28      1355911.58      6876093.92
#Sta/Elev= 30
  4446.3 2199.26  4556.1 2197.67  4561.7 2198.24  4578.2 2197.51  4600.2 2197.68
  4727.1 2195.36  4876.1 2195.17  4925.9 2193.76    4933 2192.76  4942.3 2193.09
    4948 2192.07  4964.4 2191.33    4970 2189.32  4978.1 2188.32 4990.55 2188.38
  4994.5 2187.83    4995 2187.33  5000.1 2187.33  5000.6 2187.83  5022.8 2191.91
  5040.8 2192.54  5046.9 2193.42  5082.9  2193.4  5091.9 2192.58  5106.4 2193.54
    5185 2195.45  5214.7 2194.87  5272.1 2195.77  5278.1 2195.21  5507.5 2197.18
#Mann= 3 ,-1 , 0
  4446.3     .07       0  4994.5     .07       0  5000.6     .07       0
Bank Sta=4994.5,5000.6
XS Rating Curve= 0 ,0
Exp/Cntr=0.3,0.1

Chan Stop Cuts=-1
Use User Specified Reach Order=0
Composite Channel Slope=5