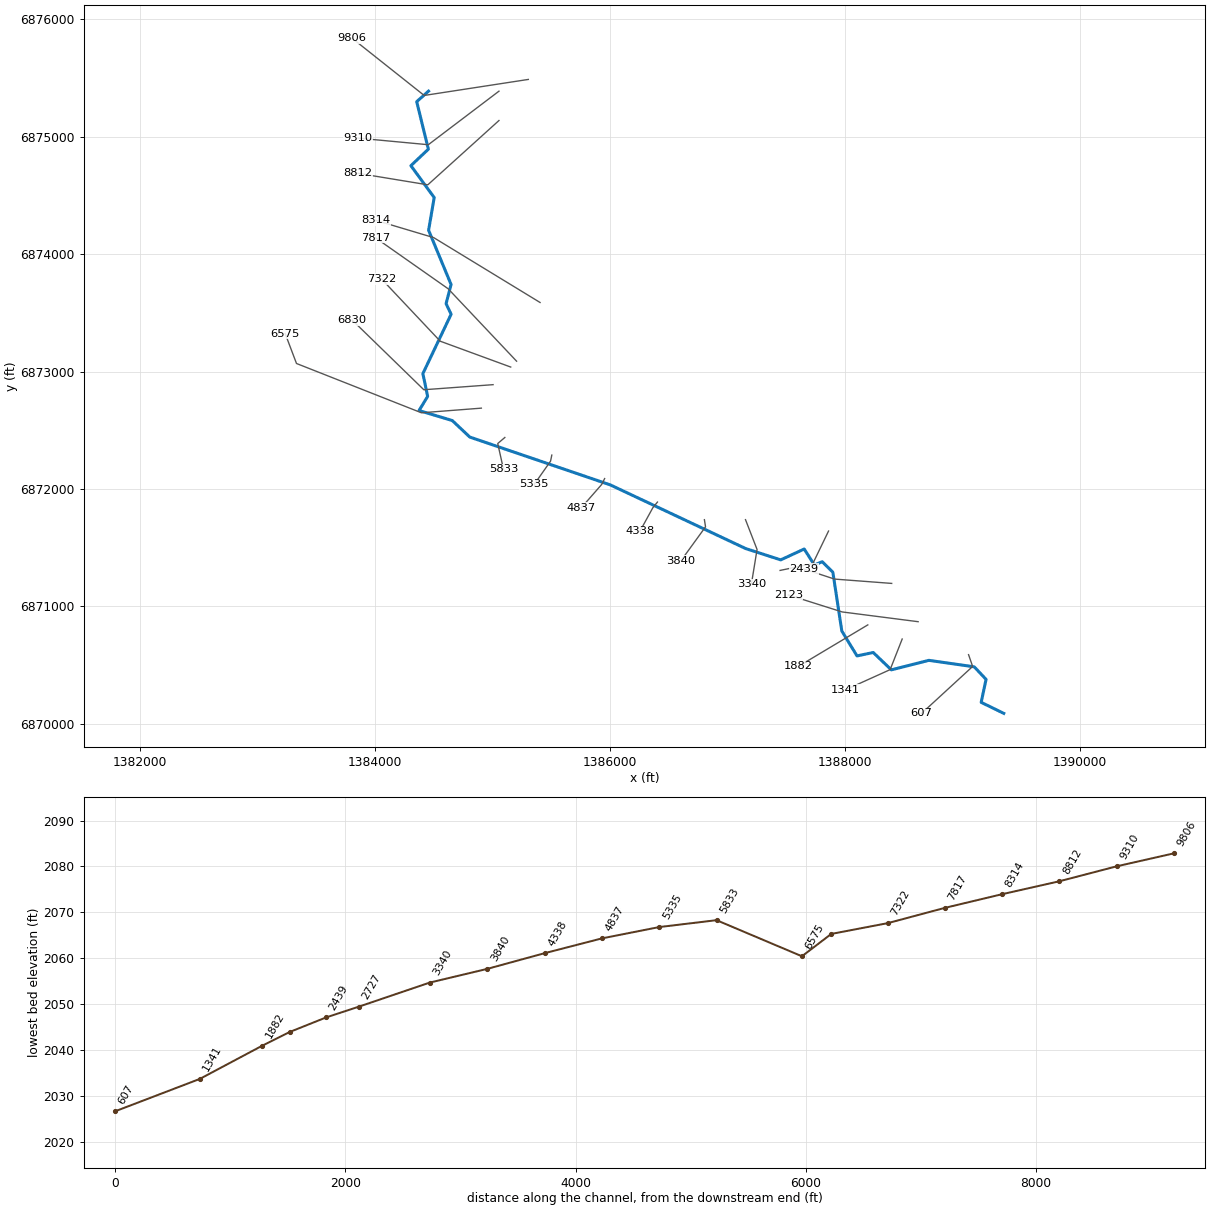
--- Sweetwater Creek Trib 27 T11.prj (project) ---

Proj Title=Sweetwater Creek Trib 27 T11 Base Level Engineering
Current Plan=p01
Default Exp/Contr=0.3,0.1
English Units
Geom File=g01
Flow File=f01
Plan File=p01
BEGIN DESCRIPTION:
Sweetwater Creek Trib 27 T11
END DESCRIPTION:

--- Sweetwater Creek Trib 27 T11.p01 (plan) ---

Plan Title=Multiple Run
Short Identifier=Multiple
Geom File=g01
Flow File=f01
Subcritical Flow
K Sum by GR= 0
Std Step Tol= 0.01
Critical Tol= 0.01
Num of Std Step Trials= 20
Max Error Tol= 0.3
Flow Tol Ratio= 0.001
Split Flow NTrial= 30
Split Flow Tol= 0.02
Split Flow Ratio= 0.02
Log Output Level= 0
Friction Slope Method= 1
Unsteady Friction Slope Method= 2
Unsteady Bridges Friction Slope Method= 1
Parabolic Critical Depth
Global Vel Dist=  1 , 1 , 1
Global Log Level= 0
CheckData=True
Encroach Param= -1, 0, 0, 0
BEGIN DESCRIPTION:
Multiple Run
END DESCRIPTION:

--- Sweetwater Creek Trib 27 T11.f01 (steady flow) ---

Flow Title=Multiple
Number of Profiles=7
Profile Names=10-year,25-year,50-year,1pct_min,100-year,1pct_plu,500-year
River Rch & RM= Sweetwater Creek,Reach-1,9806
     217     302     372     228     454     906     687
River Rch & RM= Sweetwater Creek,Reach-1,2727
     317     450     561     348     694    1384    1075
Boundary for River Rch & Prof#=Sweetwater Creek,Reach-1,1
Up Type=0
Dn Type=3
Dn Slope=0.005
Boundary for River Rch & Prof#=Sweetwater Creek,Reach-1,2
Up Type=0
Dn Type=3
Dn Slope=0.005
Boundary for River Rch & Prof#=Sweetwater Creek,Reach-1,3
Up Type=0
Dn Type=3
Dn Slope=0.005
Boundary for River Rch & Prof#=Sweetwater Creek,Reach-1,4
Up Type=0
Dn Type=3
Dn Slope=0.005
Boundary for River Rch & Prof#=Sweetwater Creek,Reach-1,5
Up Type=0
Dn Type=3
Dn Slope=0.005
Boundary for River Rch & Prof#=Sweetwater Creek,Reach-1,6
Up Type=0
Dn Type=3
Dn Slope=0.005
Boundary for River Rch & Prof#=Sweetwater Creek,Reach-1,7
Up Type=0
Dn Type=3
Dn Slope=0.005

--- Sweetwater Creek Trib 27 T11.g01 (geometry) ---

Geom Title=Existing Conditions

River Reach=Sweetwater Creek,Reach-1
Reach XY= 30
      1384455.00      6875388.00      1384354.34      6875298.59
      1384453.46      6874893.85      1384304.83      6874753.30
      1384503.20      6874481.89      1384455.52      6874203.22
      1384646.92      6873741.30      1384604.55      6873577.81
      1384647.44      6873488.00      1384406.86      6872981.87
      1384447.44      6872788.00      1384374.01      6872667.51
      1384657.30      6872582.17      1384806.50      6872441.61
      1386003.42      6872034.17      1387156.58      6871491.83
      1387455.01      6871395.53      1387655.00      6871488.00
      1387741.65      6871351.61      1387808.35      6871380.00
      1387899.14      6871290.32      1387975.25      6870789.58
      1388104.76      6870577.52      1388243.02      6870606.50
      1388397.37      6870458.67      1388716.58      6870539.62
      1389103.55      6870484.47      1389204.07      6870377.53
      1389162.47      6870181.92      1389355.00      6870088.00

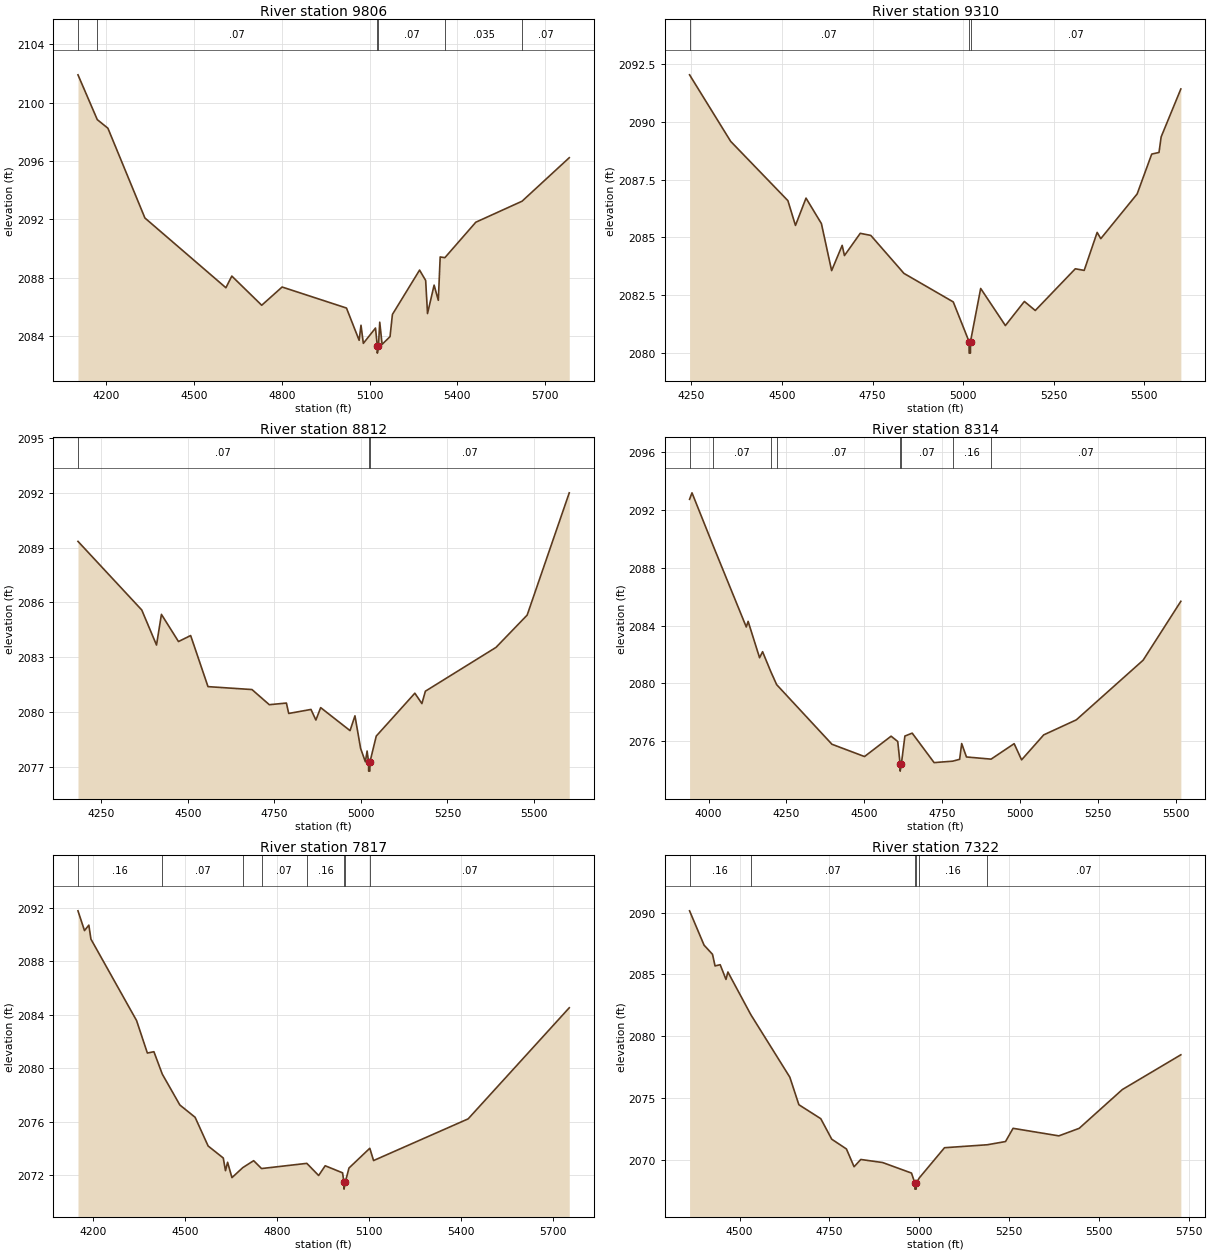
Type RM Length L Ch R = 1,9806,496,496,496
BEGIN DESCRIPTION:
Sweetwater Creek Trib 27 T11 18.0
END DESCRIPTION:
XS GIS Cut Line= 3
      1385305.00      6875488.00      1384417.95      6875351.48
      1383804.97      6875838.02
#Sta/Elev= 30
  4102.5 2101.90  4168.5 2098.83  4204.9 2098.24  4331.4 2092.09  4608.4 2087.31
  4628.6 2088.11  4730.9 2086.11  4800.6 2087.36  5020.7 2085.92  5064.0 2083.71
  5070.4 2084.74  5078.4 2083.50  5120.0 2084.55  5126.1 2083.33  5126.3 2082.83
  5130.1 2083.33  5134.5 2084.95  5142.5 2083.43  5169.7 2083.96  5177.8 2085.48
  5270.7 2088.52  5291.5 2087.81  5297.9 2085.54  5320.4 2087.49  5334.8 2086.45
  5341.2 2089.42  5357.2 2089.37  5463.0 2091.80  5621.2 2093.24  5782.6 2096.22
#Mann=6,-1,0
  4102.5   0.035       0  4168.5    0.07       0  5126.1    0.07       0
  5130.1    0.07       0  5357.2   0.035       0  5621.2    0.07       0
Bank Sta=5126.1,5130.1
Exp/Cntr=0.3,0.1

Type RM Length L Ch R = 1,9310,498,498,498
BEGIN DESCRIPTION:
Sweetwater Creek Trib 27 T11 17.0
END DESCRIPTION:
XS GIS Cut Line= 3
      1385054.98      6875387.98      1384453.23      6874931.83
      1383854.97      6874988.00
#Sta/Elev= 30
  4244.9 2092.02  4358.3 2089.15  4516.3 2086.59  4537.2 2085.52  4566.3 2086.70
  4608.8 2085.60  4637.0 2083.57  4666.1 2084.66  4672.4 2084.22  4716.0 2085.18
  4745.1 2085.09  4836.7 2083.45  4972.7 2082.22  5016.3 2080.51  5016.6 2080.01
  5020.1 2080.01  5020.3 2080.51  5048.4 2082.80  5116.6 2081.20  5169.0 2082.24
  5199.1 2081.85  5309.6 2083.65  5334.1 2083.58  5369.9 2085.22  5379.9 2084.95
  5480.3 2086.88  5520.5 2088.60  5540.6 2088.67  5546.5 2089.34  5600.9 2091.41
#Mann=3,-1,0
  4244.9    0.07       0  5016.3    0.07       0  5020.3    0.07       0
Bank Sta=5016.3,5020.3
Exp/Cntr=0.3,0.1

Type RM Length L Ch R = 1,8812,498,498,498
BEGIN DESCRIPTION:
Sweetwater Creek Trib 27 T11 16.0
END DESCRIPTION:
XS GIS Cut Line= 3
      1385054.98      6875137.99      1384448.94      6874590.23
      1383855.03      6874687.99
#Sta/Elev= 30
  4183.1 2089.34  4367.3 2085.58  4409.9 2083.66  4424.1 2085.34  4473.4 2083.85
  4508.5 2084.18  4558.6 2081.38  4685.6 2081.22  4735.7 2080.39  4785.0 2080.48
  4791.7 2079.91  4856.0 2080.13  4870.2 2079.55  4884.0 2080.23  4968.8 2078.97
  4983.0 2079.78  4999.3 2078.00  5013.1 2077.26  5018.1 2077.85  5022.3 2077.25
  5022.5 2076.75  5026.0 2076.75  5026.3 2077.25  5044.5 2078.67  5156.0 2081.02
  5176.3 2080.45  5186.4 2081.13  5390.3 2083.53  5480.3 2085.30  5601.9 2092.00
#Mann=3,-1,0
  4183.1    0.07       0  5022.3    0.07       0  5026.3    0.07       0
Bank Sta=5022.3,5026.3
Exp/Cntr=0.3,0.1

Type RM Length L Ch R = 1,8314,497,497,497
BEGIN DESCRIPTION:
Sweetwater Creek Trib 27 T11 15.0
END DESCRIPTION:
XS GIS Cut Line= 3
      1385405.02      6873587.99      1384499.25      6874140.33
      1384005.03      6874287.99
#Sta/Elev= 30
  3939.1 2092.75  3946.9 2093.20  4015.5 2089.50  4121.1 2083.91  4127.0 2084.30
  4163.8 2081.78  4173.4 2082.20  4199.8 2080.82  4218.5 2079.92  4396.1 2075.79
  4500.6 2074.94  4585.9 2076.35  4607.2 2075.98  4614.8 2074.43  4615.0 2073.93
  4618.8 2074.43  4630.2 2076.36  4653.6 2076.56  4723.9 2074.52  4783.8 2074.62
  4805.9 2074.75  4812.4 2075.84  4827.8 2074.91  4906.8 2074.76  4980.8 2075.83
  5004.7 2074.71  5075.7 2076.44  5180.3 2077.48  5394.7 2081.61  5515.8 2085.69
#Mann=8,-1,0
  3939.1    0.16       0  4015.5    0.07       0  4199.8    0.16       0
  4218.5    0.07       0  4614.8    0.07       0  4618.8    0.07       0
  4783.8    0.16       0  4906.8    0.07       0
Bank Sta=4614.8,4618.8
Exp/Cntr=0.3,0.1

Type RM Length L Ch R = 1,7817,495,495,495
BEGIN DESCRIPTION:
Sweetwater Creek Trib 27 T11 14.0
END DESCRIPTION:
XS GIS Cut Line= 3
      1385205.02      6873087.98      1384622.32      6873704.75
      1384004.98      6874138.01
#Sta/Elev= 30
  4151.5 2091.79  4172.8 2090.31  4186.9 2090.72  4193.8 2089.67  4342.7 2083.57
  4377.9 2081.14  4399.2 2081.24  4426.6 2079.56  4483.9 2077.25  4533.6 2076.33
  4576.1 2074.18  4625.5 2073.28  4632.7 2072.33  4639.6 2072.96  4653.8 2071.81
  4689.1 2072.56  4724.6 2073.08  4750.3 2072.49  4898.1 2072.88  4936.6 2071.97
  4958.0 2072.70  5014.7 2072.17  5019.2 2071.45  5019.4 2070.95  5023.2 2071.45
  5035.6 2072.53  5103.5 2074.01  5115.8 2073.09  5424.3 2076.21  5754.2 2084.53
#Mann=8,-1,0
  4151.5    0.16       0  4426.6    0.07       0  4689.1    0.16       0
  4750.3    0.07       0  4898.1    0.16       0  5019.2    0.07       0
  5023.2    0.16       0  5103.5    0.07       0
Bank Sta=5019.2,5023.2
Exp/Cntr=0.3,0.1

Type RM Length L Ch R = 1,7322,492,492,492
BEGIN DESCRIPTION:
Sweetwater Creek Trib 27 T11 13.0
END DESCRIPTION:
XS GIS Cut Line= 3
      1385154.99      6873038.00      1384554.68      6873258.13
      1384055.01      6873787.99
#Sta/Elev= 30
  4360.6 2090.15  4401.0 2087.37  4424.5 2086.63  4431.5 2085.69  4445.8 2085.79
  4462.0 2084.60  4467.3 2085.20  4531.1 2081.75  4639.7 2076.69  4664.9 2074.46
  4725.9 2073.33  4756.4 2071.67  4797.3 2070.88  4818.6 2069.44  4837.2 2070.03
  4898.2 2069.78  4978.4 2068.93  4987.7 2068.13  4988.0 2067.63  4991.5 2067.63
  4991.7 2068.13  5000.5 2068.55  5070.3 2070.98  5189.4 2071.22  5240.2 2071.48
  5261.2 2072.55  5388.7 2071.94  5445.3 2072.55  5565.5 2075.69  5728.3 2078.50
#Mann=6,-1,0
  4360.6    0.16       0  4531.1    0.07       0  4987.7    0.07       0
  4991.7    0.07       0  5000.5    0.16       0  5189.4    0.07       0
Bank Sta=4987.7,4991.7
Exp/Cntr=0.3,0.1

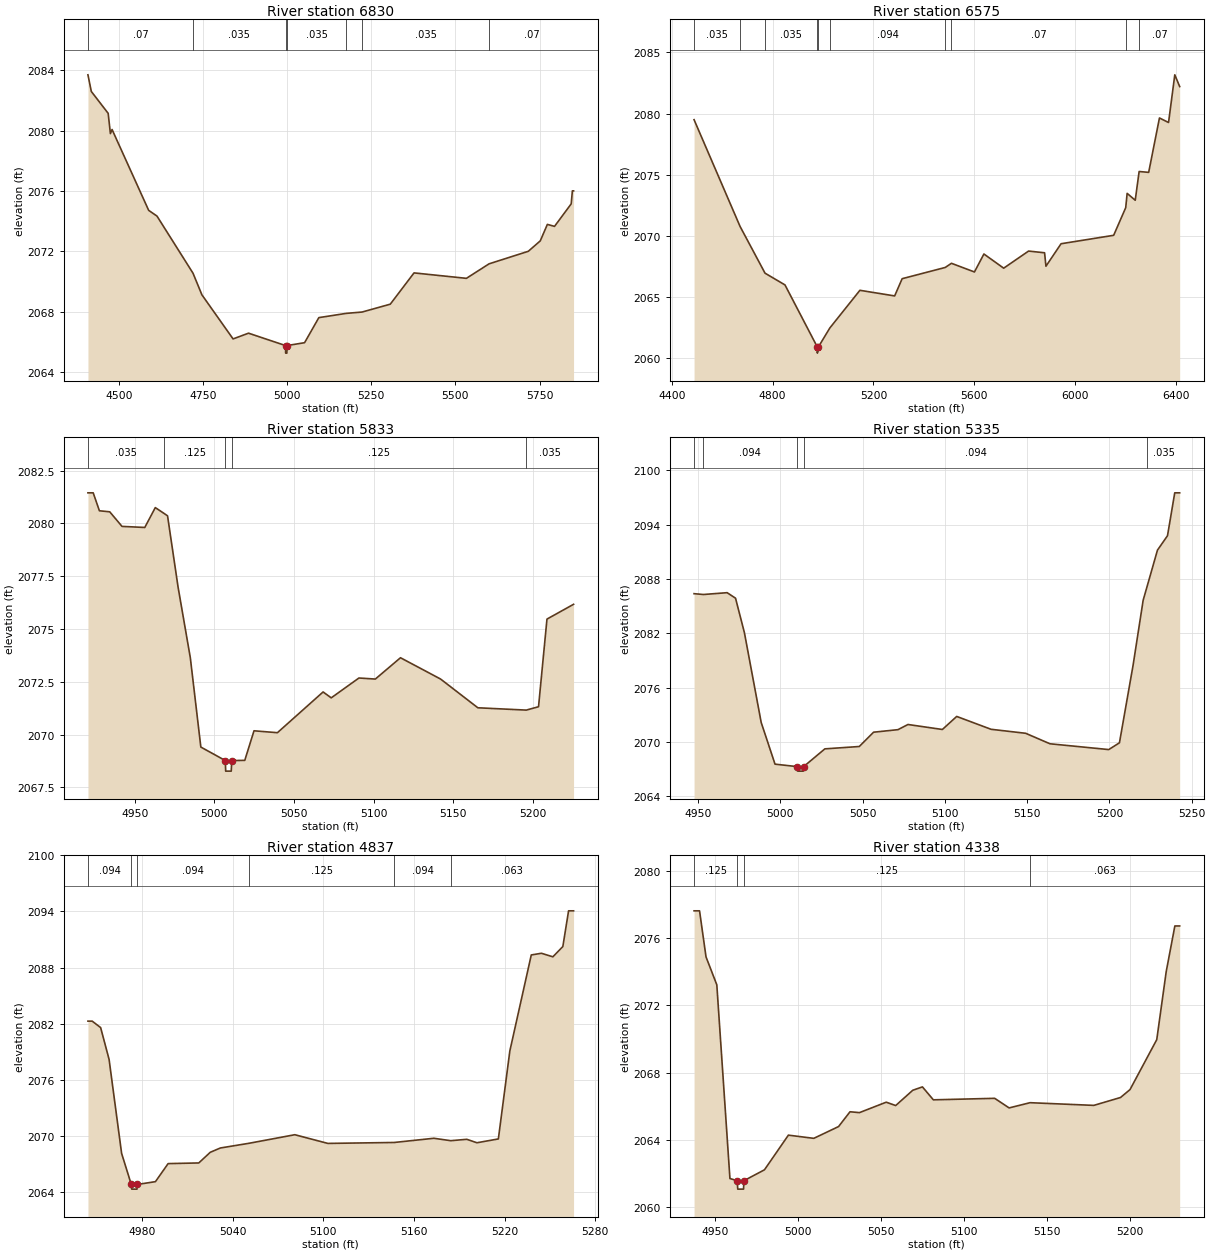
Type RM Length L Ch R = 1,6830,255,255,255
BEGIN DESCRIPTION:
Sweetwater Creek Trib 27 T11 12.0
END DESCRIPTION:
XS GIS Cut Line= 3
      1385004.96      6872888.00      1384414.95      6872844.66
      1383805.02      6873437.98
#Sta/Elev= 30
  4408.4 2083.69  4418.4 2082.59  4468.5 2081.14  4475.1 2079.80  4480.1 2080.07
  4588.8 2074.72  4613.5 2074.34  4720.5 2070.56  4746.9 2069.13  4839.5 2066.21
  4885.4 2066.59  4995.5 2065.77  4995.7 2065.27  4999.2 2065.27  4999.5 2065.77
  5051.9 2065.96  5094.3 2067.62  5175.5 2067.90  5222.8 2067.99  5306.5 2068.51
  5377.0 2070.58  5532.6 2070.22  5599.9 2071.18  5716.5 2072.01  5752.0 2072.70
  5773.1 2073.79  5794.4 2073.66  5843.9 2075.15  5847.4 2076.01  5850.9 2076.01
#Mann=7,-1,0
  4408.4    0.07       0  4720.5   0.035       0  4995.5   0.035       0
  4999.5   0.035       0  5175.5    0.07       0  5222.8   0.035       0
  5599.9    0.07       0
Bank Sta=4995.5,4999.5
Exp/Cntr=0.3,0.1

Type RM Length L Ch R = 1,6575,742,742,742
BEGIN DESCRIPTION:
Sweetwater Creek Trib 27 T11 11.0
END DESCRIPTION:
XS GIS Cut Line= 4
      1384905.02      6872688.00      1384394.44      6872648.48
      1383330.27      6873068.33      1383233.89      6873323.11
#Sta/Elev= 30
  4487.9 2079.50  4670.7 2070.76  4769.8 2066.94  4849.0 2065.98  4977.4 2060.90
  4977.6 2060.40  4981.4 2060.90  5027.2 2062.46  5146.5 2065.54  5284.5 2065.08
  5314.3 2066.49  5485.5 2067.41  5510.0 2067.75  5601.4 2067.04  5639.0 2068.51
  5717.5 2067.35  5816.4 2068.75  5879.9 2068.61  5885.3 2067.51  5945.4 2069.35
  6154.3 2070.04  6202.1 2072.30  6207.8 2073.47  6239.9 2072.91  6255.4 2075.26
  6293.3 2075.19  6336.1 2079.64  6372.2 2079.27  6397.0 2083.17  6416.4 2082.21
#Mann=10,-1,0
  4487.9   0.035       0  4670.7    0.07       0  4769.8   0.035       0
  4977.4   0.035       0  4981.4   0.035       0  5027.2   0.094       0
  5485.5   0.035       0  5510.0    0.07       0  6202.1   0.035       0
  6255.4    0.07       0
Bank Sta=4977.4,4981.4
Exp/Cntr=0.3,0.1

Type RM Length L Ch R = 1,5833,498,498,498
BEGIN DESCRIPTION:
Sweetwater Creek Trib 27 T11 10.0
END DESCRIPTION:
XS GIS Cut Line= 3
      1385105.01      6872438.01      1385044.45      6872386.67
      1385093.57      6872166.48
#Sta/Elev= 30
  4920.6 2081.45  4923.9 2081.45  4927.8 2080.60  4934.3 2080.55  4942.0 2079.86
  4956.3 2079.81  4962.9 2080.75  4968.3 2080.48  4970.6 2080.36  4977.2 2076.99
  4984.9 2073.64  4991.5 2069.41  5006.9 2068.77  5007.1 2068.27  5010.6 2068.27
  5010.9 2068.77  5019.1 2068.78  5024.9 2070.18  5039.6 2070.09  5068.3 2072.02
  5073.4 2071.74  5090.8 2072.68  5101.1 2072.63  5116.9 2073.64  5142.1 2072.63
  5165.5 2071.27  5195.9 2071.16  5203.6 2071.32  5208.9 2075.47  5225.6 2076.17
#Mann=5,-1,0
  4920.6   0.035       0  4968.3   0.125       0  5006.9    0.07       0
  5010.9   0.125       0  5195.9   0.035       0
Bank Sta=5006.9,5010.9
Exp/Cntr=0.3,0.1

Type RM Length L Ch R = 1,5335,498,498,498
BEGIN DESCRIPTION:
Sweetwater Creek Trib 27 T11 9.0
END DESCRIPTION:
XS GIS Cut Line= 3
      1385505.00      6872288.01      1385494.46      6872236.69
      1385355.02      6872038.04
#Sta/Elev= 30
  4947.6 2086.37  4953.3 2086.28  4967.7 2086.48  4972.8 2085.87  4978.2 2082.06
  4988.4 2072.14  4996.8 2067.54  5010.2 2067.27  5010.5 2066.77  5014.0 2066.77
  5014.2 2067.27  5027.1 2069.23  5048.0 2069.49  5056.7 2071.07  5071.5 2071.35
  5077.6 2071.92  5098.5 2071.37  5107.2 2072.81  5128.1 2071.39  5149.1 2070.95
  5163.9 2069.79  5199.6 2069.15  5206.1 2069.90  5214.4 2078.48  5220.5 2085.64
  5223.0 2087.23  5229.2 2091.18  5235.3 2092.77  5239.7 2097.51  5242.7 2097.51
#Mann=5,-1,0
  4947.6   0.035       0  4953.3   0.094       0  5010.2    0.07       0
  5014.2   0.094       0  5223.0   0.035       0
Bank Sta=5010.2,5014.2
Exp/Cntr=0.3,0.1

Type RM Length L Ch R = 1,4837,499,499,499
BEGIN DESCRIPTION:
Sweetwater Creek Trib 27 T11 8.0
END DESCRIPTION:
XS GIS Cut Line= 3
      1385954.99      6872087.99      1385930.00      6872037.99
      1385755.03      6871838.03
#Sta/Elev= 30
  4944.1 2082.27  4946.9 2082.27  4952.5 2081.58  4958.1 2078.18  4966.4 2068.12
  4972.8 2064.80  4973.1 2064.30  4976.6 2064.30  4976.8 2064.80  4988.8 2065.10
  4997.2 2067.03  5017.5 2067.10  5025.1 2068.24  5031.8 2068.70  5051.0 2069.21
  5081.1 2070.12  5103.0 2069.19  5146.9 2069.29  5173.2 2069.74  5184.4 2069.48
  5195.0 2069.63  5201.7 2069.26  5215.9 2069.67  5223.5 2079.08  5237.7 2089.35
  5244.4 2089.53  5252.0 2089.15  5258.6 2090.25  5262.4 2094.07  5265.7 2094.07
#Mann=6,-1,0
  4944.1   0.094       0  4972.8    0.07       0  4976.8   0.094       0
  5051.0   0.125       0  5146.9   0.094       0  5184.4   0.063       0
Bank Sta=4972.8,4976.8
Exp/Cntr=0.3,0.1

Type RM Length L Ch R = 1,4338,498,498,498
BEGIN DESCRIPTION:
Sweetwater Creek Trib 27 T11 7.0
END DESCRIPTION:
XS GIS Cut Line= 3
      1386405.02      6871888.03      1386365.54      6871839.31
      1386254.98      6871637.97
#Sta/Elev= 30
  4937.3 2077.62  4940.6 2077.62  4944.5 2074.88  4951.0 2073.22  4958.9 2061.70
  4963.3 2061.57  4963.6 2061.07  4967.1 2061.07  4967.3 2061.57  4979.7 2062.22
  4994.1 2064.28  5009.4 2064.09  5024.3 2064.79  5031.2 2065.67  5036.9 2065.62
  5053.0 2066.24  5058.7 2066.04  5069.0 2066.95  5074.8 2067.15  5081.4 2066.38
  5118.3 2066.47  5127.0 2065.90  5139.6 2066.21  5178.0 2066.05  5194.1 2066.52
  5199.8 2066.99  5215.9 2069.96  5221.6 2074.01  5226.8 2076.72  5229.7 2076.72
#Mann=4,-1,0
  4937.3   0.125       0  4963.3    0.07       0  4967.3   0.125       0
  5139.6   0.063       0
Bank Sta=4963.3,4967.3
Exp/Cntr=0.3,0.1

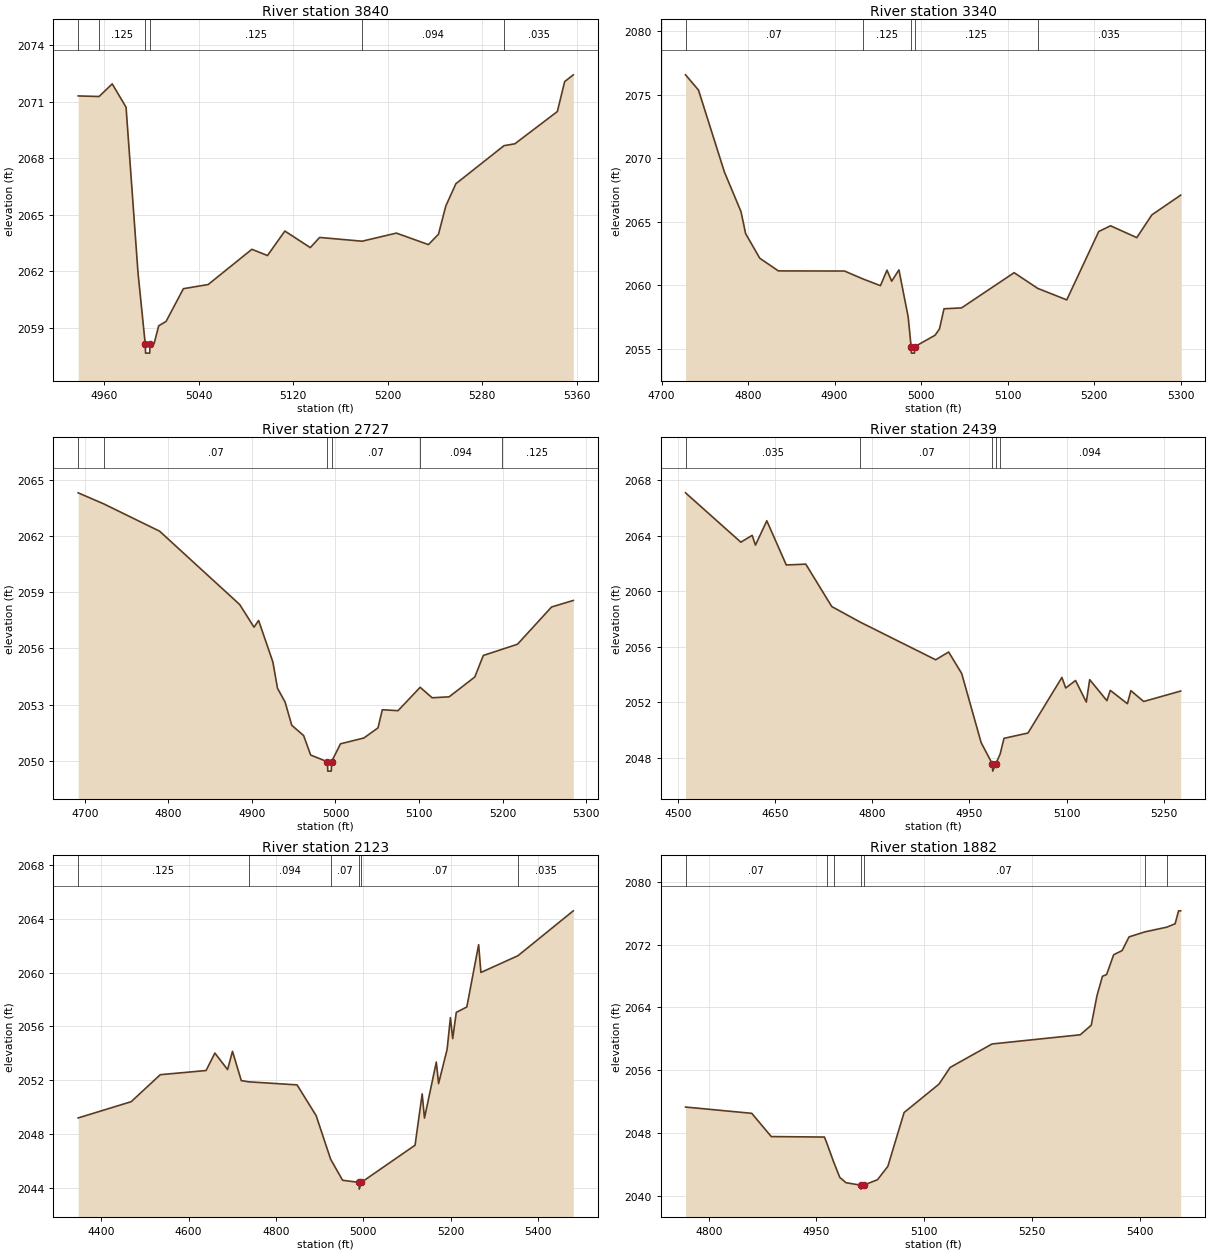
Type RM Length L Ch R = 1,3840,500,500,500
BEGIN DESCRIPTION:
Sweetwater Creek Trib 27 T11 6.0
END DESCRIPTION:
XS GIS Cut Line= 3
      1386805.00      6871737.97      1386814.55      6871676.92
      1386605.01      6871388.01
#Sta/Elev= 30
  4938.2 2071.30  4955.9 2071.27  4967.0 2071.94  4978.7 2070.70  4988.8 2061.92
  4994.9 2058.15  4995.2 2057.65  4998.7 2057.65  4998.9 2058.15  5002.4 2058.15
  5006.3 2059.10  5012.5 2059.33  5027.2 2061.07  5048.1 2061.29  5085.1 2063.16
  5098.3 2062.83  5113.0 2064.13  5134.5 2063.25  5142.4 2063.79  5178.3 2063.59
  5207.3 2064.02  5234.4 2063.41  5242.9 2063.96  5249.1 2065.46  5257.6 2066.64
  5298.3 2068.66  5307.5 2068.76  5343.4 2070.47  5349.6 2072.06  5356.9 2072.42
#Mann=6,-1,0
  4938.2   0.094       0  4955.9   0.125       0  4994.9    0.07       0
  4998.9   0.125       0  5178.3   0.094       0  5298.3   0.035       0
Bank Sta=4994.9,4998.9
Exp/Cntr=0.3,0.1

Type RM Length L Ch R = 1,3340,613,613,613
BEGIN DESCRIPTION:
Sweetwater Creek Trib 27 T11 5.0
END DESCRIPTION:
XS GIS Cut Line= 3
      1387154.99      6871738.04      1387253.40      6871484.15
      1387205.00      6871187.98
#Sta/Elev= 30
  4727.7 2076.56  4742.7 2075.36  4772.6 2068.92  4791.8 2065.80  4797.2 2064.06
  4813.5 2062.13  4835.0 2061.13  4911.5 2061.12  4932.7 2060.50  4953.0 2059.97
  4960.6 2061.19  4966.0 2060.32  4974.4 2061.21  4985.1 2057.51  4988.5 2055.16
  4988.8 2054.66  4992.3 2054.66  4992.5 2055.16  5016.2 2056.07  5021.3 2056.57
  5026.5 2058.15  5046.8 2058.22  5107.6 2060.99  5134.7 2059.76  5168.4 2058.85
  5205.4 2064.23  5219.0 2064.68  5249.4 2063.75  5266.8 2065.54  5300.1 2067.09
#Mann=5,-1,0
  4727.7    0.07       0  4932.7   0.125       0  4988.5    0.07       0
  4992.5   0.125       0  5134.7   0.035       0
Bank Sta=4988.5,4992.5
Exp/Cntr=0.3,0.1

Type RM Length L Ch R = 1,2727,288,288,288
BEGIN DESCRIPTION:
Sweetwater Creek Trib 27 T11 4.1
END DESCRIPTION:
XS GIS Cut Line= 3
      1387862.30      6871641.03      1387728.29      6871363.71
      1387449.56      6871305.69
#Sta/Elev= 30
  4692.0 2064.31  4722.6 2063.72  4789.5 2062.26  4885.4 2058.34  4902.5 2057.13
  4908.0 2057.49  4925.1 2055.27  4930.6 2053.87  4939.7 2053.13  4947.7 2051.89
  4961.9 2051.34  4970.3 2050.30  4990.4 2049.94  4990.8 2049.44  4995.0 2049.44
  4995.3 2049.94  5006.0 2050.90  5034.0 2051.21  5050.9 2051.75  5056.1 2052.72
  5074.9 2052.67  5101.4 2053.92  5115.7 2053.36  5136.1 2053.41  5166.8 2054.47
  5177.0 2055.62  5198.8 2055.94  5217.9 2056.22  5258.7 2058.21  5284.7 2058.56
#Mann=6,-1,0
  4692.0   0.035       0  4722.6    0.07       0  4990.4    0.07       0
  4995.3    0.07       0  5101.4   0.094       0  5198.8   0.125       0
Bank Sta=4990.4,4995.3
Exp/Cntr=0.3,0.1

Type RM Length L Ch R = 1,2439,316,316,316
BEGIN DESCRIPTION:
Sweetwater Creek Trib 27 T11 4.0
END DESCRIPTION:
XS GIS Cut Line= 3
      1388400.16      6871195.03      1387913.15      6871231.94
      1387650.81      6871318.31
#Sta/Elev= 30
  4511.6 2067.08  4597.0 2063.53  4614.5 2064.02  4619.6 2063.32  4637.1 2065.07
  4667.2 2061.89  4697.3 2061.95  4737.4 2058.90  4781.7 2057.77  4897.9 2055.07
  4917.9 2055.63  4938.0 2054.09  4968.1 2049.11  4985.6 2047.56  4986.0 2047.06
  4990.6 2047.56  4997.5 2048.30  5003.4 2049.42  5040.4 2049.80  5092.8 2053.80
  5098.7 2053.04  5113.9 2053.58  5130.5 2052.03  5135.7 2053.64  5162.3 2052.13
  5167.5 2052.87  5194.0 2051.91  5199.3 2052.85  5219.1 2052.07  5276.2 2052.82
#Mann=5,-1,0
  4511.6   0.035       0  4781.7    0.07       0  4985.6    0.07       0
  4990.6    0.07       0  4997.5   0.094       0
Bank Sta=4985.6,4990.6
Exp/Cntr=0.3,0.1

Type RM Length L Ch R = 1,2123,241,241,241
BEGIN DESCRIPTION:
Sweetwater Creek Trib 27 T11 3.0
END DESCRIPTION:
XS GIS Cut Line= 3
      1388625.45      6870868.92      1387978.17      6870952.07
      1387519.58      6871097.18
#Sta/Elev= 30
  4347.4 2049.19  4468.8 2050.40  4535.4 2052.41  4640.2 2052.72  4660.4 2054.02
  4689.5 2052.79  4700.7 2054.15  4720.9 2051.97  4737.7 2051.88  4848.6 2051.65
  4892.3 2049.36  4925.4 2046.12  4952.8 2044.55  4990.6 2044.39  4991.0 2043.89
  4995.6 2044.39  5118.7 2047.16  5135.0 2050.98  5140.3 2049.18  5167.4 2053.35
  5172.6 2051.75  5192.1 2054.30  5199.7 2056.66  5204.9 2055.10  5213.1 2057.05
  5237.2 2057.45  5264.3 2062.09  5269.5 2060.02  5354.4 2061.27  5481.0 2064.61
#Mann=6,-1,0
  4347.4   0.125       0  4737.7   0.094       0  4925.4    0.07       0
  4990.6    0.07       0  4995.6    0.07       0  5354.4   0.035       0
Bank Sta=4990.6,4995.6
Exp/Cntr=0.3,0.1

Type RM Length L Ch R = 1,1882,541,541,541
BEGIN DESCRIPTION:
Sweetwater Creek Trib 27 T11 2.0
END DESCRIPTION:
XS GIS Cut Line= 3
      1388196.78      6870841.75      1387997.39      6870722.55
      1387605.04      6870488.02
#Sta/Elev= 30
  4767.7 2051.32  4859.9 2050.52  4887.1 2047.56  4961.1 2047.50  4964.5 2046.71
  4974.1 2044.29  4982.5 2042.36  4991.1 2041.69  5011.6 2041.37  5011.9 2040.87
  5015.6 2041.37  5035.0 2042.07  5049.4 2043.77  5072.0 2050.62  5120.6 2054.24
  5136.2 2056.37  5194.5 2059.35  5317.3 2060.52  5332.6 2061.74  5340.6 2065.50
  5348.2 2067.97  5354.0 2068.19  5363.8 2070.71  5375.6 2071.24  5385.2 2072.98
  5407.3 2073.62  5437.7 2074.22  5449.4 2074.65  5454.2 2076.30  5457.1 2076.30
#Mann=7,-1,0
  4767.7    0.07       0  4964.5   0.035       0  4974.1    0.07       0
  5011.6    0.07       0  5015.6    0.07       0  5407.3   0.035       0
  5437.7   0.063       0
Bank Sta=5011.6,5015.6
Exp/Cntr=0.3,0.1

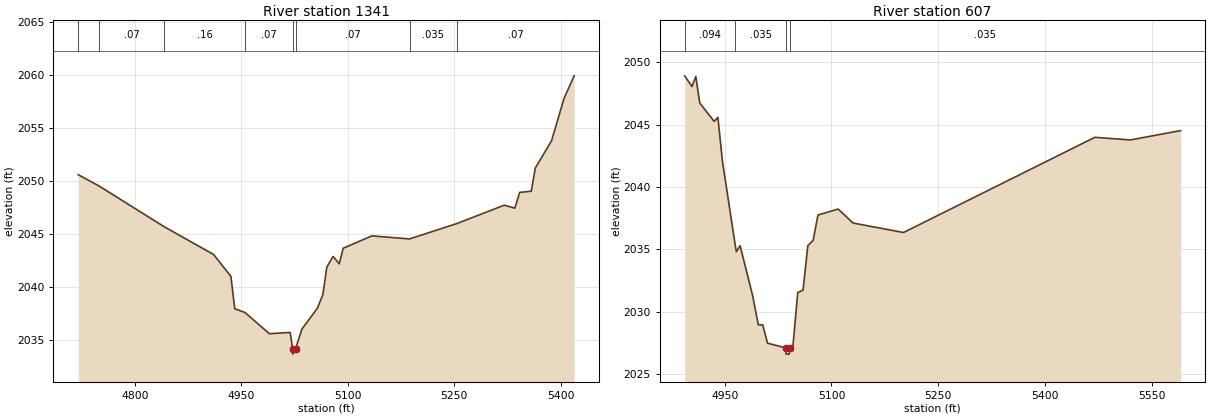
Type RM Length L Ch R = 1,1341,734,734,734
BEGIN DESCRIPTION:
Sweetwater Creek Trib 27 T11 1.0
END DESCRIPTION:
XS GIS Cut Line= 3
      1388489.68      6870721.43      1388387.04      6870460.60
      1388005.02      6870288.01
#Sta/Elev= 30
  4719.7 2050.60  4748.9 2049.54  4841.1 2045.68  4910.7 2043.06  4935.1 2040.99
  4940.5 2037.94  4955.0 2037.58  4989.3 2035.58  5018.6 2035.70  5022.2 2034.15
  5022.4 2033.65  5026.2 2034.15  5035.2 2036.01  5057.1 2037.99  5064.8 2039.28
  5070.3 2041.86  5079.1 2042.88  5087.9 2042.18  5093.4 2043.65  5133.9 2044.82
  5187.0 2044.53  5254.1 2045.99  5320.5 2047.72  5335.6 2047.44  5342.4 2048.93
  5358.7 2049.04  5364.4 2051.23  5387.3 2053.80  5404.9 2057.80  5419.2 2059.94
#Mann=8,-1,0
  4719.7   0.094       0  4748.9    0.07       0  4841.1    0.16       0
  4955.0    0.07       0  5022.2    0.07       0  5026.2    0.07       0
  5187.0   0.035       0  5254.1    0.07       0
Bank Sta=5022.2,5026.2
Exp/Cntr=0.3,0.1

Type RM Length L Ch R = 1,607,0,0,0
BEGIN DESCRIPTION:
Sweetwater Creek Trib 27 T11 0.1
END DESCRIPTION:
XS GIS Cut Line= 3
      1389054.99      6870588.04      1389089.85      6870487.62
      1388654.99      6870087.99
#Sta/Elev= 30
  4893.7 2048.92  4904.0 2048.06  4909.3 2048.87  4914.9 2046.74  4935.1 2045.27
  4940.4 2045.59  4946.7 2042.09  4964.5 2035.44  4966.3 2034.82  4971.6 2035.30
  4989.0 2031.35  4997.2 2028.96  5003.4 2028.96  5010.1 2027.49  5035.9 2027.11
  5036.3 2026.61  5040.6 2026.61  5041.0 2027.11  5045.9 2027.30  5052.6 2031.55
  5060.0 2031.73  5066.8 2035.31  5074.2 2035.73  5081.0 2037.76  5109.4 2038.24
  5130.3 2037.12  5201.2 2036.36  5470.1 2043.99  5520.0 2043.78  5590.6 2044.53
#Mann=4,-1,0
  4893.7   0.094       0  4964.5   0.035       0  5035.9   0.035       0
  5041.0   0.035       0
Bank Sta=5035.9,5041
Exp/Cntr=0.3,0.1

Chan Stop Cuts=-1