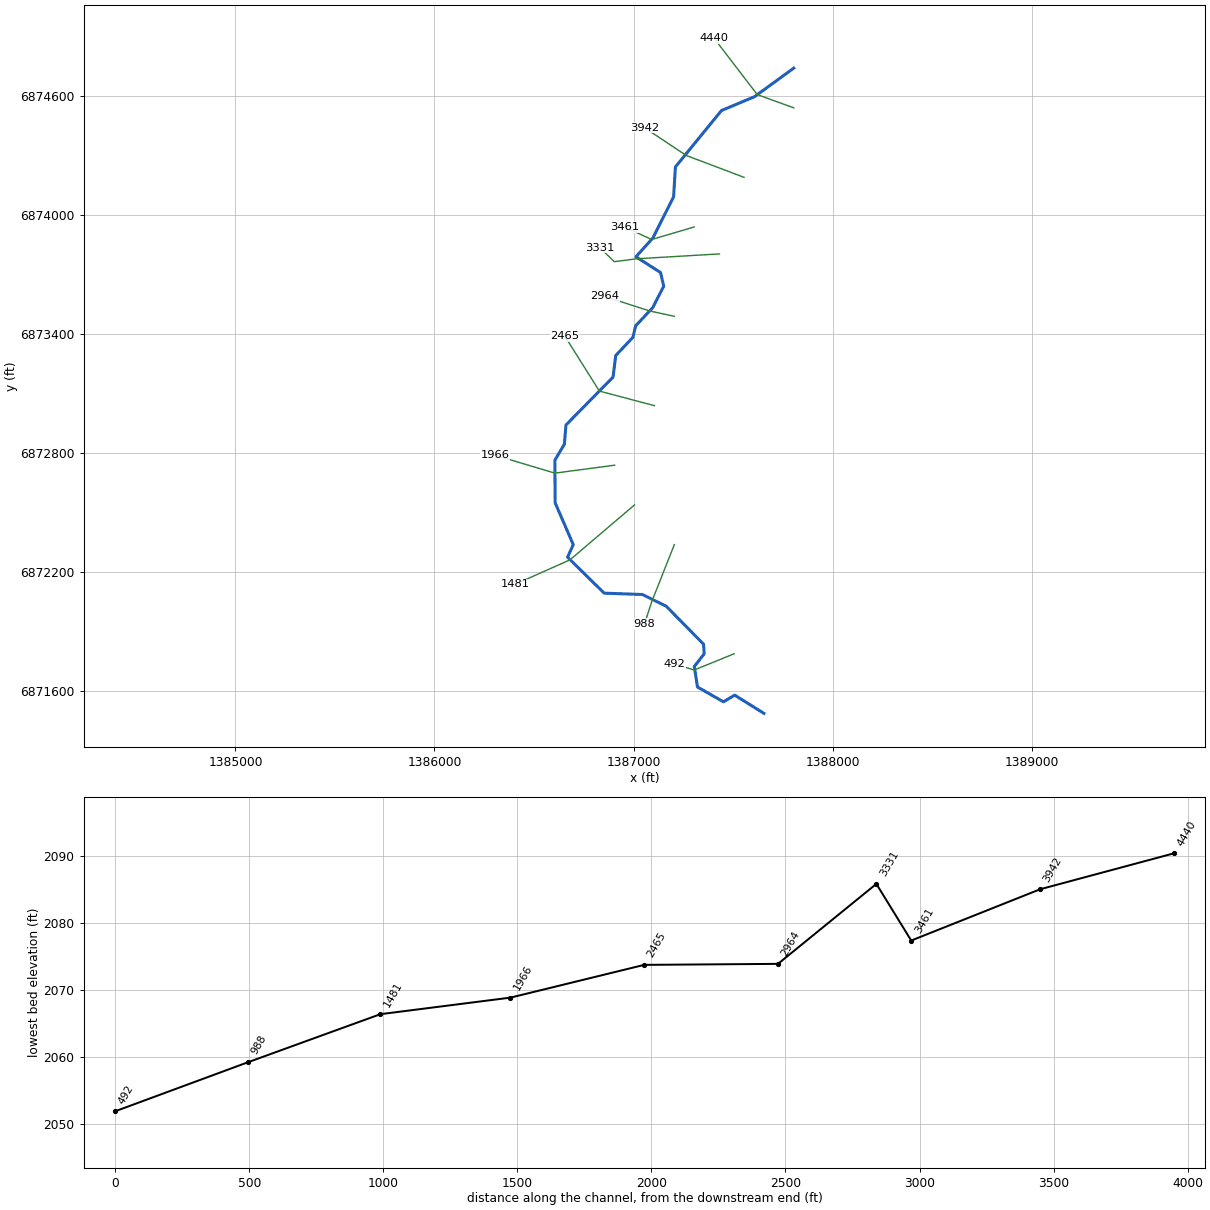
--- Sweetwater Creek Trib 27 T11_1.prj (project) ---

Proj Title=Sweetwater Creek Trib 27 T11_1 Base Level Engineering
Current Plan=p01
Default Exp/Contr=0.3,0.1
English Units
Geom File=g01
Flow File=f01
Plan File=p01
BEGIN DESCRIPTION:
Sweetwater Creek Trib 27 T11_1
END DESCRIPTION:

--- Sweetwater Creek Trib 27 T11_1.p01 (plan) ---

Plan Title=Multiple Run
Short Identifier=Multiple
Geom File=g01
Flow File=f01
Subcritical Flow
K Sum by GR= 0
Std Step Tol= 0.01
Critical Tol= 0.01
Num of Std Step Trials= 20
Max Error Tol= 0.3
Flow Tol Ratio= 0.001
Split Flow NTrial= 30
Split Flow Tol= 0.02
Split Flow Ratio= 0.02
Log Output Level= 0
Friction Slope Method= 1
Unsteady Friction Slope Method= 2
Unsteady Bridges Friction Slope Method= 1
Parabolic Critical Depth
Global Vel Dist=  1 , 1 , 1
Global Log Level= 0
CheckData=True
Encroach Param= -1, 0, 0, 0
BEGIN DESCRIPTION:
Multiple Run
END DESCRIPTION:

--- Sweetwater Creek Trib 27 T11_1.f01 (steady flow) ---

Flow Title=Multiple
Number of Profiles=7
Profile Names=10-year,25-year,50-year,1pct_min,100-year,1pct_plu,500-year
River Rch & RM= Sweetwater Creek,Reach-1,4440
     106     142     170     102     203     405     293
River Rch & RM= Sweetwater Creek,Reach-1,492
     144     196     239     145     289     577     429
Boundary for River Rch & Prof#=Sweetwater Creek,Reach-1,1
Up Type=0
Dn Type=3
Dn Slope=0.005
Boundary for River Rch & Prof#=Sweetwater Creek,Reach-1,2
Up Type=0
Dn Type=3
Dn Slope=0.005
Boundary for River Rch & Prof#=Sweetwater Creek,Reach-1,3
Up Type=0
Dn Type=3
Dn Slope=0.005
Boundary for River Rch & Prof#=Sweetwater Creek,Reach-1,4
Up Type=0
Dn Type=3
Dn Slope=0.005
Boundary for River Rch & Prof#=Sweetwater Creek,Reach-1,5
Up Type=0
Dn Type=3
Dn Slope=0.005
Boundary for River Rch & Prof#=Sweetwater Creek,Reach-1,6
Up Type=0
Dn Type=3
Dn Slope=0.005
Boundary for River Rch & Prof#=Sweetwater Creek,Reach-1,7
Up Type=0
Dn Type=3
Dn Slope=0.005

--- Sweetwater Creek Trib 27 T11_1.g01 (geometry) ---

Geom Title=Existing Conditions

River Reach=Sweetwater Creek,Reach-1
Reach XY= 30
      1387805.00      6874738.00      1387607.29      6874593.85
      1387441.76      6874524.39      1387210.47      6874240.45
      1387201.24      6874089.56      1387096.82      6873881.94
      1387011.99      6873787.78      1387135.73      6873708.47
      1387151.70      6873639.76      1387096.85      6873531.95
      1387010.87      6873440.28      1386996.82      6873381.96
      1386910.54      6873290.42      1386897.14      6873181.83
      1386660.52      6872940.43      1386652.64      6872843.98
      1386604.80      6872763.08      1386606.22      6872548.50
      1386697.20      6872337.90      1386668.64      6872274.66
      1386852.55      6872093.46      1387044.50      6872086.80
      1387164.68      6872027.24      1387351.73      6871836.64
      1387355.00      6871788.00      1387305.32      6871724.08
      1387321.25      6871620.86      1387451.76      6871546.24
      1387508.23      6871579.78      1387655.00      6871488.00

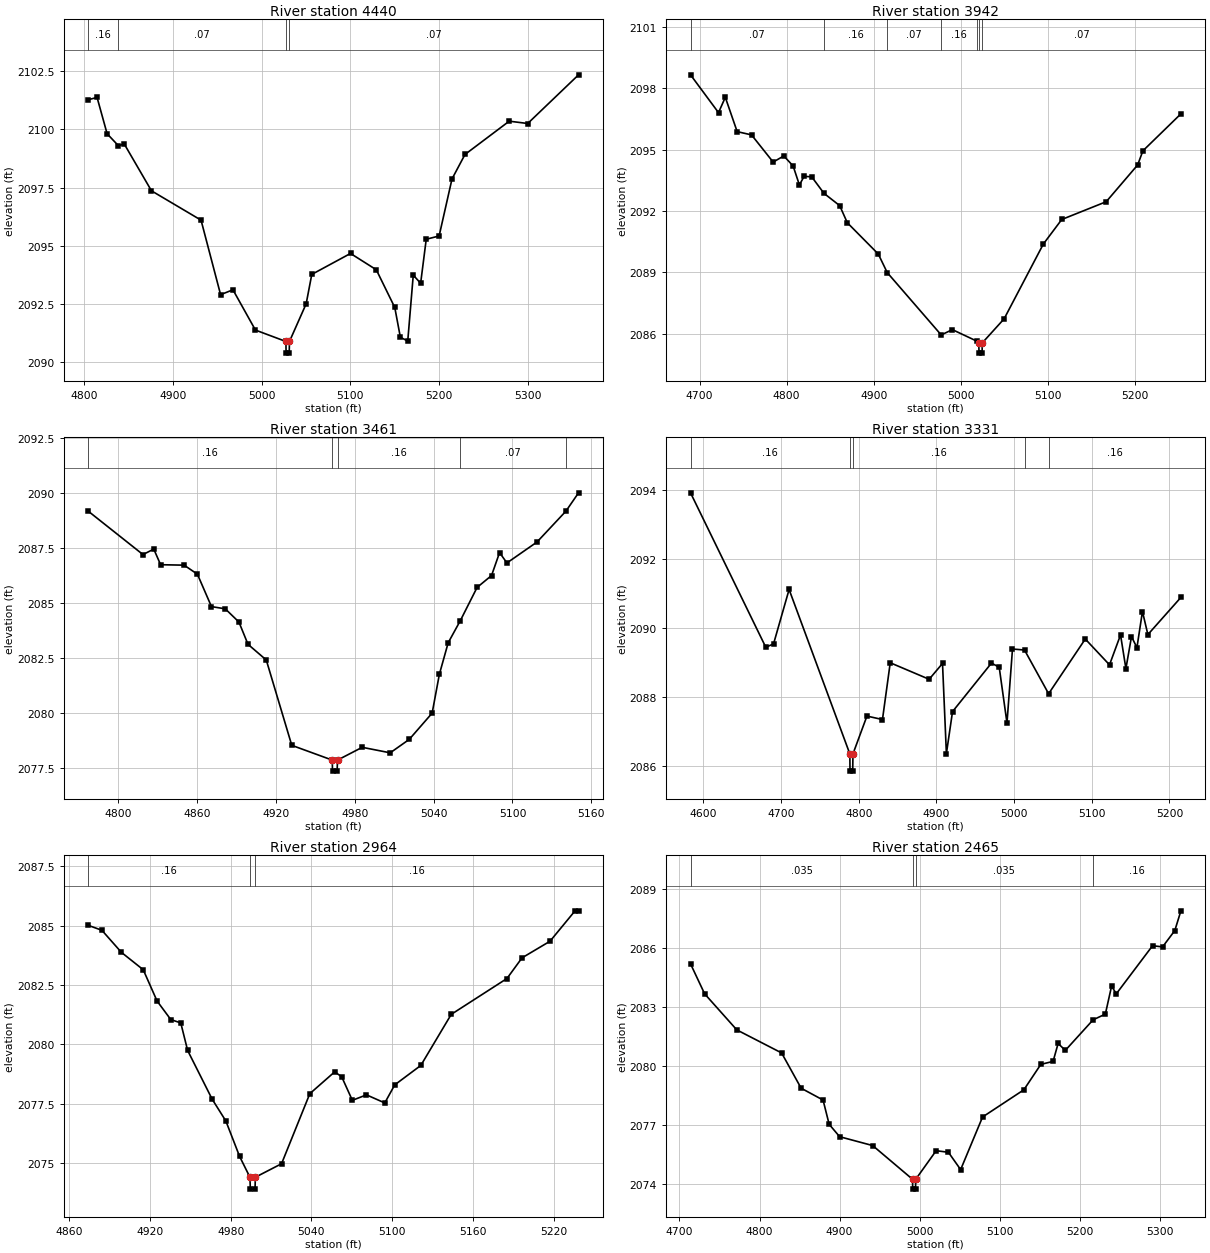
Type RM Length L Ch R = 1,4440,498,498,498
BEGIN DESCRIPTION:
Sweetwater Creek Trib 27 T11_1 8.0
END DESCRIPTION:
XS GIS Cut Line= 3
      1387805.02      6874537.99      1387621.66      6874604.67
      1387404.98      6874888.02
#Sta/Elev= 30
  4804.9 2101.27  4814.9 2101.37  4826.2 2099.81  4838.8 2099.30  4845.5 2099.37
  4876.1 2097.36  4931.9 2096.10  4953.9 2092.90  4967.8 2093.11  4993.1 2091.38
  5027.4 2090.89  5027.6 2090.39  5031.1 2090.39  5031.4 2090.89  5050.2 2092.51
  5056.5 2093.77  5100.1 2094.67  5129.1 2093.97  5149.9 2092.35  5156.2 2091.07
  5164.5 2090.91  5170.7 2093.74  5179.0 2093.39  5185.3 2095.28  5199.8 2095.42
  5214.3 2097.87  5228.9 2098.92  5278.7 2100.35  5299.5 2100.25  5356.7 2102.34
#Mann=4,-1,0
  4804.9    0.16       0  4838.8    0.07       0  5027.4    0.07       0
  5031.4    0.07       0
Bank Sta=5027.4,5031.4
Exp/Cntr=0.3,0.1

Type RM Length L Ch R = 1,3942,481,481,481
BEGIN DESCRIPTION:
Sweetwater Creek Trib 27 T11_1 7.0
END DESCRIPTION:
XS GIS Cut Line= 3
      1387555.00      6874188.00      1387264.88      6874298.05
      1387054.96      6874438.02
#Sta/Elev= 30
  4689.7 2098.66  4721.8 2096.81  4729.6 2097.56  4743.2 2095.88  4759.7 2095.72
  4784.5 2094.39  4796.7 2094.69  4807.4 2094.20  4814.6 2093.27  4820.0 2093.69
  4828.7 2093.67  4842.8 2092.86  4860.8 2092.26  4869.6 2091.42  4905.1 2089.89
  4915.4 2088.98  4977.3 2085.93  4990.1 2086.19  5018.0 2085.63  5020.4 2085.54
  5020.7 2085.04  5024.2 2085.04  5024.4 2085.54  5049.5 2086.72  5094.5 2090.38
  5115.6 2091.58  5166.6 2092.45  5202.7 2094.25  5208.7 2094.94  5252.3 2096.75
#Mann=7,-1,0
  4689.7    0.07       0  4842.8    0.16       0  4915.4    0.07       0
  4977.3    0.16       0  5018.0    0.07       0  5020.4    0.07       0
  5024.4    0.07       0
Bank Sta=5020.4,5024.4
Exp/Cntr=0.3,0.1

Type RM Length L Ch R = 1,3461,130,130,130
BEGIN DESCRIPTION:
Sweetwater Creek Trib 27 T11_1 6.0
END DESCRIPTION:
XS GIS Cut Line= 3
      1387304.97      6873937.99      1387091.32      6873874.78
      1386954.97      6873938.01
#Sta/Elev= 30
  4777.2 2089.17  4818.9 2087.20  4827.1 2087.45  4832.3 2086.74  4850.2 2086.72
  4860.3 2086.31  4871.0 2084.84  4881.5 2084.74  4891.9 2084.14  4898.8 2083.13
  4912.7 2082.42  4932.1 2078.55  4962.9 2077.88  4963.1 2077.38  4966.6 2077.38
  4966.9 2077.88  4985.7 2078.46  5007.0 2078.21  5021.5 2078.82  5038.9 2080.01
  5044.4 2081.77  5051.1 2083.20  5060.4 2084.21  5073.1 2085.71  5084.1 2086.25
  5090.2 2087.29  5095.8 2086.82  5118.7 2087.77  5140.7 2089.17  5150.3 2090.00
#Mann=5,-1,0
  4777.2    0.16       0  4962.9    0.07       0  4966.9    0.16       0
  5060.4    0.07       0  5140.7    0.16       0
Bank Sta=4962.9,4966.9
Exp/Cntr=0.3,0.1

Type RM Length L Ch R = 1,3331,367,367,367
BEGIN DESCRIPTION:
Sweetwater Creek Trib 27 T11_1 4154
END DESCRIPTION:
XS GIS Cut Line= 4
      1387431.70      6873802.27      1387015.83      6873777.68
      1386903.24      6873763.20      1386830.63      6873833.67
#Sta/Elev= 30
  4583.4 2093.93  4680.3 2089.44  4690.3 2089.54  4710.3 2091.12  4788.5 2086.34
  4788.7 2085.84  4792.2 2085.84  4792.5 2086.34  4810.5 2087.44  4830.5 2087.34
  4840.5 2088.99  4890.6 2088.51  4907.8 2088.97  4912.8 2086.35  4920.7 2087.57
  4970.8 2088.98  4980.8 2088.86  4990.8 2087.24  4997.9 2089.39  5013.4 2089.36
  5044.4 2088.09  5091.6 2089.68  5122.8 2088.93  5137.0 2089.80  5143.9 2088.82
  5151.1 2089.75  5158.1 2089.43  5165.2 2090.48  5172.2 2089.81  5214.7 2090.89
#Mann=5,-1,0
  4583.4    0.16       0  4788.5    0.07       0  4792.5    0.16       0
  5013.4    0.07       0  5044.4    0.16       0
Bank Sta=4788.5,4792.5
Exp/Cntr=0.3,0.1

Type RM Length L Ch R = 1,2964,499,499,499
BEGIN DESCRIPTION:
Sweetwater Creek Trib 27 T11_1 5.0
END DESCRIPTION:
XS GIS Cut Line= 3
      1387205.01      6873488.00      1387081.94      6873514.55
      1386855.03      6873587.99
#Sta/Elev= 30
  4874.1 2085.01  4884.3 2084.80  4898.8 2083.87  4915.0 2083.14  4925.3 2081.82
  4935.5 2081.04  4942.9 2080.90  4948.0 2079.74  4966.2 2077.69  4976.4 2076.77
  4986.6 2075.28  4994.3 2074.40  4994.6 2073.90  4998.1 2073.90  4998.3 2074.40
  5017.8 2074.97  5038.8 2077.92  5057.3 2078.84  5062.5 2078.63  5070.4 2077.64
  5080.9 2077.87  5094.5 2077.53  5101.9 2078.29  5121.3 2079.11  5143.9 2081.26
  5185.3 2082.77  5196.5 2083.64  5217.3 2084.34  5235.9 2085.62  5238.5 2085.62
#Mann=3,-1,0
  4874.1    0.16       0  4994.3    0.07       0  4998.3    0.16       0
Bank Sta=4994.3,4998.3
Exp/Cntr=0.3,0.1

Type RM Length L Ch R = 1,2465,499,499,499
BEGIN DESCRIPTION:
Sweetwater Creek Trib 27 T11_1 4.0
END DESCRIPTION:
XS GIS Cut Line= 3
      1387105.04      6873037.99      1386828.39      6873111.31
      1386655.01      6873387.98
#Sta/Elev= 30
  4713.8 2085.18  4731.4 2083.66  4771.6 2081.83  4827.6 2080.66  4852.0 2078.87
  4879.4 2078.27  4887.0 2077.04  4900.1 2076.41  4941.4 2075.96  4991.2 2074.25
  4991.4 2073.75  4994.9 2073.75  4995.2 2074.25  5020.7 2075.70  5036.0 2075.62
  5051.3 2074.74  5078.7 2077.41  5130.3 2078.79  5151.5 2080.08  5166.8 2080.23
  5173.1 2081.14  5182.1 2080.79  5216.8 2082.34  5232.1 2082.63  5239.9 2084.05
  5245.8 2083.66  5291.1 2086.10  5303.6 2086.04  5318.9 2086.87  5326.5 2087.87
#Mann=4,-1,0
  4713.8   0.035       0  4991.2   0.035       0  4995.2   0.035       0
  5216.8    0.16       0
Bank Sta=4991.2,4995.2
Exp/Cntr=0.3,0.1

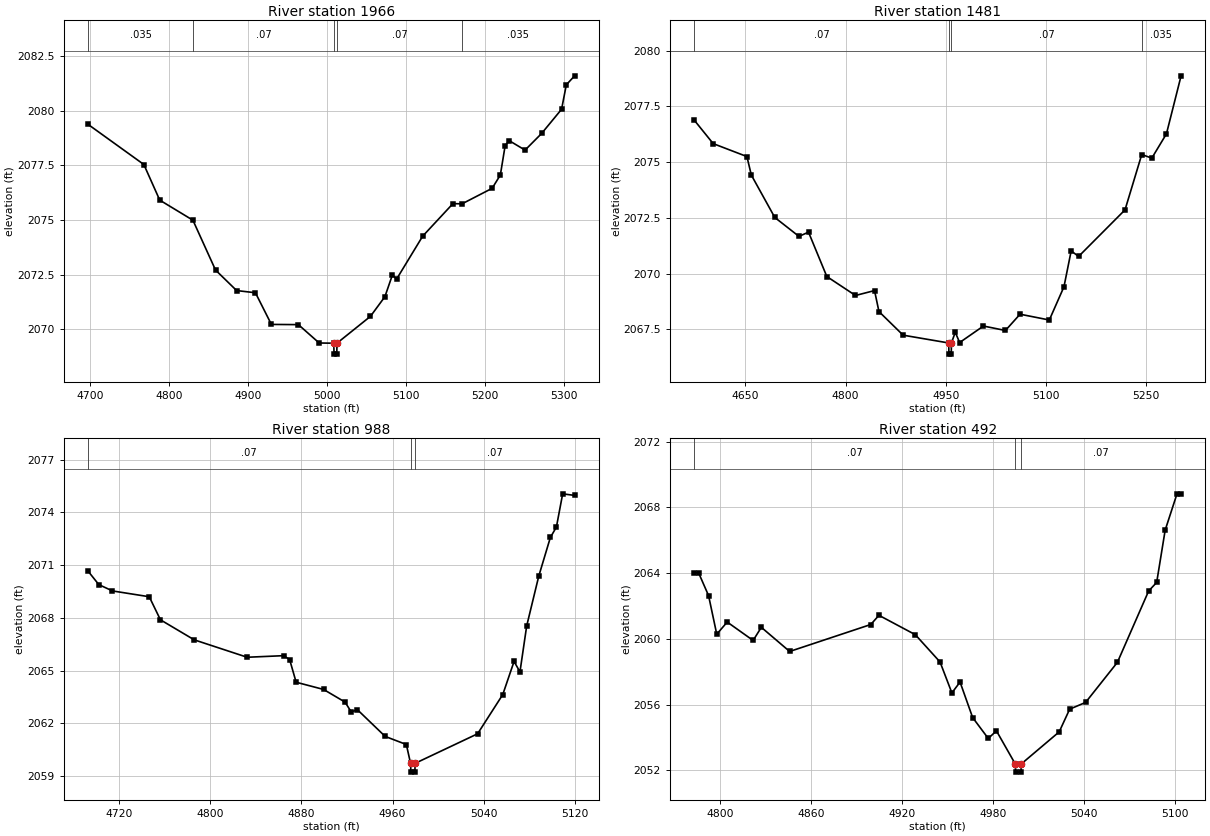
Type RM Length L Ch R = 1,1966,485,485,485
BEGIN DESCRIPTION:
Sweetwater Creek Trib 27 T11_1 3.0
END DESCRIPTION:
XS GIS Cut Line= 3
      1386905.03      6872738.00      1386604.88      6872698.05
      1386304.98      6872788.01
#Sta/Elev= 30
  4697.2 2079.38  4767.9 2077.54  4788.0 2075.91  4830.0 2074.99  4858.6 2072.71
  4885.3 2071.77  4909.1 2071.67  4929.3 2070.22  4963.5 2070.21  4989.8 2069.37
  5008.3 2069.36  5008.6 2068.86  5012.1 2068.86  5012.3 2069.36  5054.7 2070.59
  5073.0 2071.49  5082.5 2072.49  5087.7 2072.29  5120.8 2074.26  5159.1 2075.75
  5170.6 2075.74  5208.7 2076.45  5219.1 2077.06  5225.2 2078.41  5230.4 2078.63
  5250.4 2078.20  5271.3 2078.96  5296.6 2080.07  5302.6 2081.19  5313.1 2081.60
#Mann=5,-1,0
  4697.2   0.035       0  4830.0    0.07       0  5008.3    0.07       0
  5012.3    0.07       0  5170.6   0.035       0
Bank Sta=5008.3,5012.3
Exp/Cntr=0.3,0.1

Type RM Length L Ch R = 1,1481,493,493,493
BEGIN DESCRIPTION:
Sweetwater Creek Trib 27 T11_1 2.0
END DESCRIPTION:
XS GIS Cut Line= 3
      1387004.98      6872537.98      1386680.77      6872261.33
      1386405.00      6872138.00
#Sta/Elev= 30
  4573.8 2076.87  4601.8 2075.83  4652.3 2075.25  4658.9 2074.42  4694.0 2072.52
  4730.2 2071.67  4744.5 2071.86  4771.9 2069.87  4814.8 2069.02  4843.3 2069.24
  4849.9 2068.30  4886.1 2067.24  4954.4 2066.89  4954.6 2066.39  4958.1 2066.39
  4958.4 2066.89  4964.1 2067.37  4970.7 2066.91  5006.3 2067.65  5039.2 2067.45
  5061.1 2068.18  5104.9 2067.92  5126.8 2069.41  5137.6 2071.02  5148.7 2070.77
  5218.2 2072.86  5243.2 2075.34  5258.3 2075.18  5280.2 2076.27  5302.1 2078.87
#Mann=4,-1,0
  4573.8    0.07       0  4954.4    0.07       0  4958.4    0.07       0
  5243.2   0.035       0
Bank Sta=4954.4,4958.4
Exp/Cntr=0.3,0.1

Type RM Length L Ch R = 1,988,496,496,496
BEGIN DESCRIPTION:
Sweetwater Creek Trib 27 T11_1 1.0
END DESCRIPTION:
XS GIS Cut Line= 3
      1387205.01      6872338.02      1387091.97      6872052.05
      1387055.00      6871938.00
#Sta/Elev= 30
  4692.5 2070.66  4702.0 2069.89  4714.0 2069.53  4746.3 2069.20  4756.1 2067.89
  4785.8 2066.75  4832.3 2065.76  4864.3 2065.85  4869.6 2065.63  4875.3 2064.34
  4899.4 2063.93  4918.3 2063.21  4923.7 2062.65  4929.1 2062.78  4953.5 2061.26
  4972.1 2060.80  4975.8 2059.73  4976.1 2059.23  4979.6 2059.23  4979.8 2059.73
  5034.7 2061.41  5056.8 2063.64  5066.7 2065.52  5071.9 2064.93  5077.8 2067.54
  5088.4 2070.37  5098.6 2072.57  5103.9 2073.16  5109.4 2075.05  5119.9 2074.96
#Mann=3,-1,0
  4692.5    0.07       0  4975.8    0.07       0  4979.8    0.07       0
Bank Sta=4975.8,4979.8
Exp/Cntr=0.3,0.1

Type RM Length L Ch R = 1,492,0,0,0
BEGIN DESCRIPTION:
Sweetwater Creek Trib 27 T11_1 2760
END DESCRIPTION:
XS GIS Cut Line= 3
      1387504.97      6871787.99      1387304.30      6871706.20
      1387204.97      6871738.01
#Sta/Elev= 30
  4783.3 2064.03  4786.0 2064.03  4792.6 2062.64  4798.0 2060.29  4804.9 2061.03
  4822.0 2059.91  4827.4 2060.71  4846.1 2059.24  4899.6 2060.88  4905.0 2061.44
  4929.0 2060.26  4945.3 2058.60  4953.1 2056.72  4958.5 2057.38  4966.8 2055.22
  4977.1 2053.95  4982.5 2054.41  4994.9 2052.40  4995.2 2051.90  4998.7 2051.90
  4998.9 2052.40  5023.9 2054.35  5030.8 2055.73  5041.3 2056.14  5062.3 2058.58
  5082.9 2062.92  5088.2 2063.44  5093.8 2066.62  5101.6 2068.83  5104.3 2068.83
#Mann=3,-1,0
  4783.3    0.07       0  4994.9    0.07       0  4998.9    0.07       0
Bank Sta=4994.9,4998.9
Exp/Cntr=0.3,0.1

Chan Stop Cuts=-1