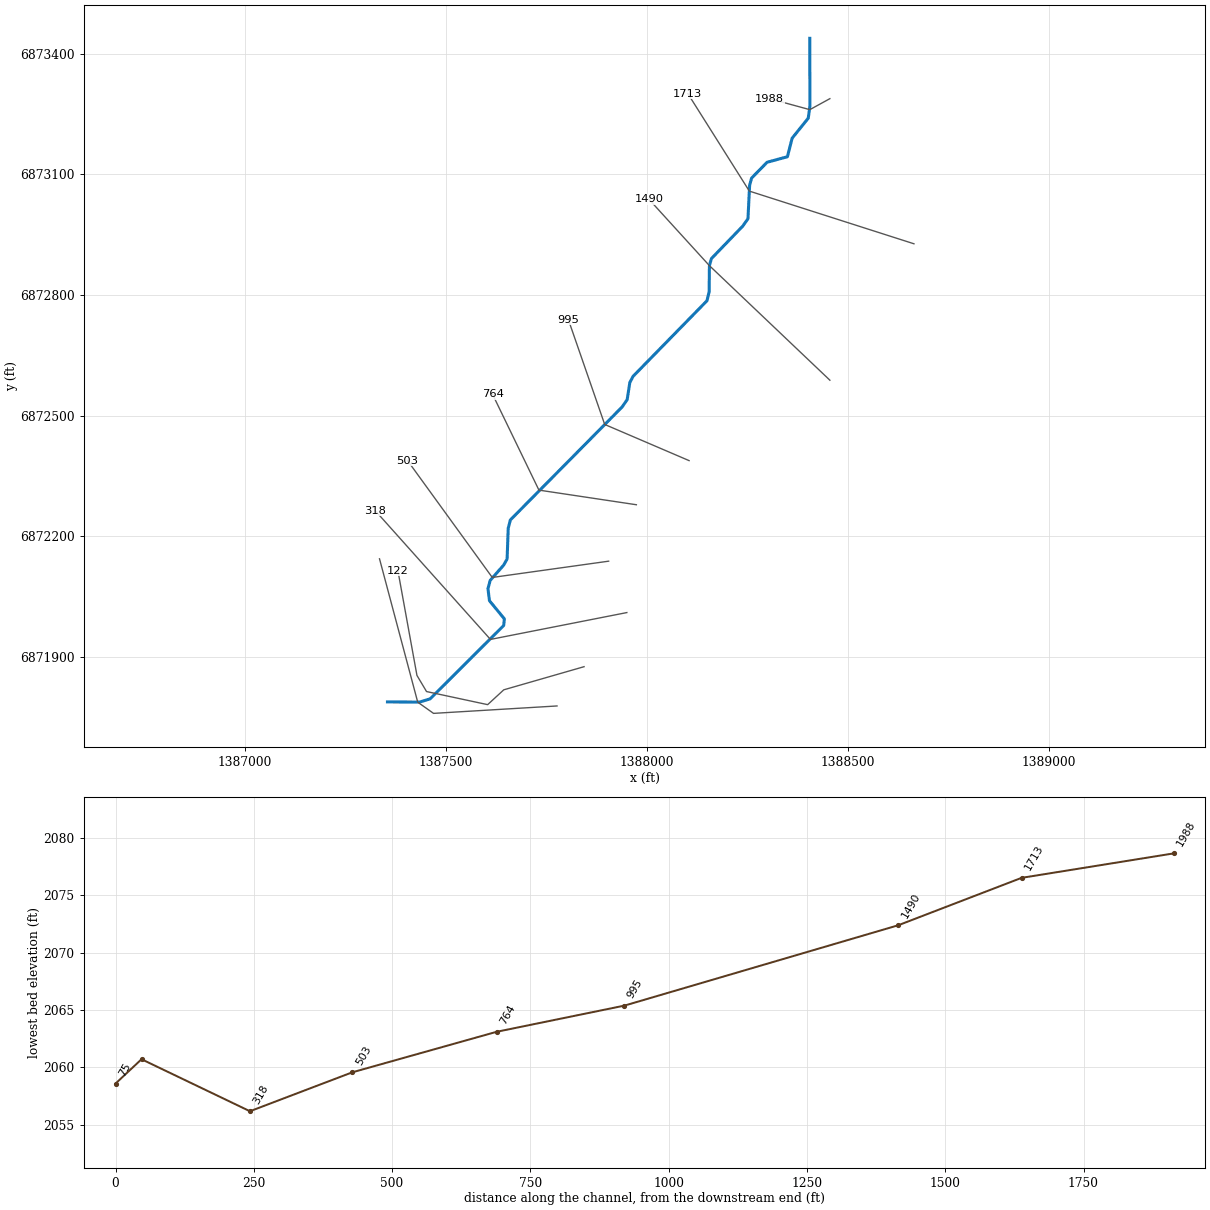
--- Sweetwater Creek Trib 27 T11_1T.prj (project) ---

Proj Title=Sweetwater Creek Trib 27 T11_1T Base Level Engineering
Current Plan=p01
Default Exp/Contr=0.3,0.1
English Units
Geom File=g01
Flow File=f01
Plan File=p01
Y Axis Title=Elevation
X Axis Title(PF)=Main Channel Distance
X Axis Title(XS)=Station
BEGIN DESCRIPTION:
Sweetwater Creek Trib 27 T11_1T
END DESCRIPTION:
DSS Export Rating Curves= 0
DSS Export Rating Curve Sorted= 0
DSS Export Volume Flow Curves= 0
DXF OffsetX= 0
DXF OffsetY= 0
DXF ScaleX= 1
DXF ScaleY= 10

--- Sweetwater Creek Trib 27 T11_1T.p01 (plan) ---

Plan Title=Multiple Run
Short Identifier=Multiple
Geom File=g01
Flow File=f01
Subcritical Flow
K Sum by GR= 0
Std Step Tol= 0.01
Critical Tol= 0.01
Num of Std Step Trials= 20
Max Error Tol= 0.3
Flow Tol Ratio= 0.001
Split Flow NTrial= 30
Split Flow Tol= 0.02
Split Flow Ratio= 0.02
Log Output Level= 0
Friction Slope Method= 1
Unsteady Friction Slope Method= 2
Unsteady Bridges Friction Slope Method= 1
Parabolic Critical Depth
Global Vel Dist=  1 , 1 , 1
Global Log Level= 0
CheckData=True
Encroach Param= -1, 0, 0, 0
BEGIN DESCRIPTION:
Multiple Run
END DESCRIPTION:

--- Sweetwater Creek Trib 27 T11_1T.f01 (steady flow) ---

Flow Title=Multiple
Number of Profiles=7
Profile Names=10-year,25-year,50-year,1pct_min,100-year,1pct_plu,500-year
River Rch & RM= Sweetwater Creek,Reach-1,1988
      66      86     101      59     119     237     165
Boundary for River Rch & Prof#=Sweetwater Creek,Reach-1,1
Up Type=0
Dn Type=3
Dn Slope=0.005
Boundary for River Rch & Prof#=Sweetwater Creek,Reach-1,2
Up Type=0
Dn Type=3
Dn Slope=0.005
Boundary for River Rch & Prof#=Sweetwater Creek,Reach-1,3
Up Type=0
Dn Type=3
Dn Slope=0.005
Boundary for River Rch & Prof#=Sweetwater Creek,Reach-1,4
Up Type=0
Dn Type=3
Dn Slope=0.005
Boundary for River Rch & Prof#=Sweetwater Creek,Reach-1,5
Up Type=0
Dn Type=3
Dn Slope=0.005
Boundary for River Rch & Prof#=Sweetwater Creek,Reach-1,6
Up Type=0
Dn Type=3
Dn Slope=0.005
Boundary for River Rch & Prof#=Sweetwater Creek,Reach-1,7
Up Type=0
Dn Type=3
Dn Slope=0.005

--- Sweetwater Creek Trib 27 T11_1T.g01 (geometry) ---

Geom Title=Existing Conditions

River Reach=Sweetwater Creek,Reach-1
Reach XY= 30
      1388405.00      6873438.00      1388405.41      6873269.64
      1388401.27      6873239.52      1388361.28      6873189.84
      1388349.38      6873143.62      1388298.92      6873129.85
      1388260.46      6873090.66      1388255.49      6873072.90
      1388251.37      6872989.50      1388238.51      6872971.26
      1388160.54      6872890.42      1388155.53      6872872.78
      1388154.87      6872808.06      1388149.48      6872785.57
      1387965.78      6872597.68      1387957.64      6872582.36
      1387951.02      6872539.65      1387938.35      6872521.33
      1387660.52      6872240.43      1387655.24      6872219.72
      1387652.50      6872143.56      1387644.05      6872128.35
      1387610.40      6872090.17      1387604.89      6872069.54
      1387608.62      6872039.63      1387645.67      6871994.55
      1387643.89      6871977.95      1387461.22      6871795.74
      1387435.14      6871787.67      1387355.00      6871788.00

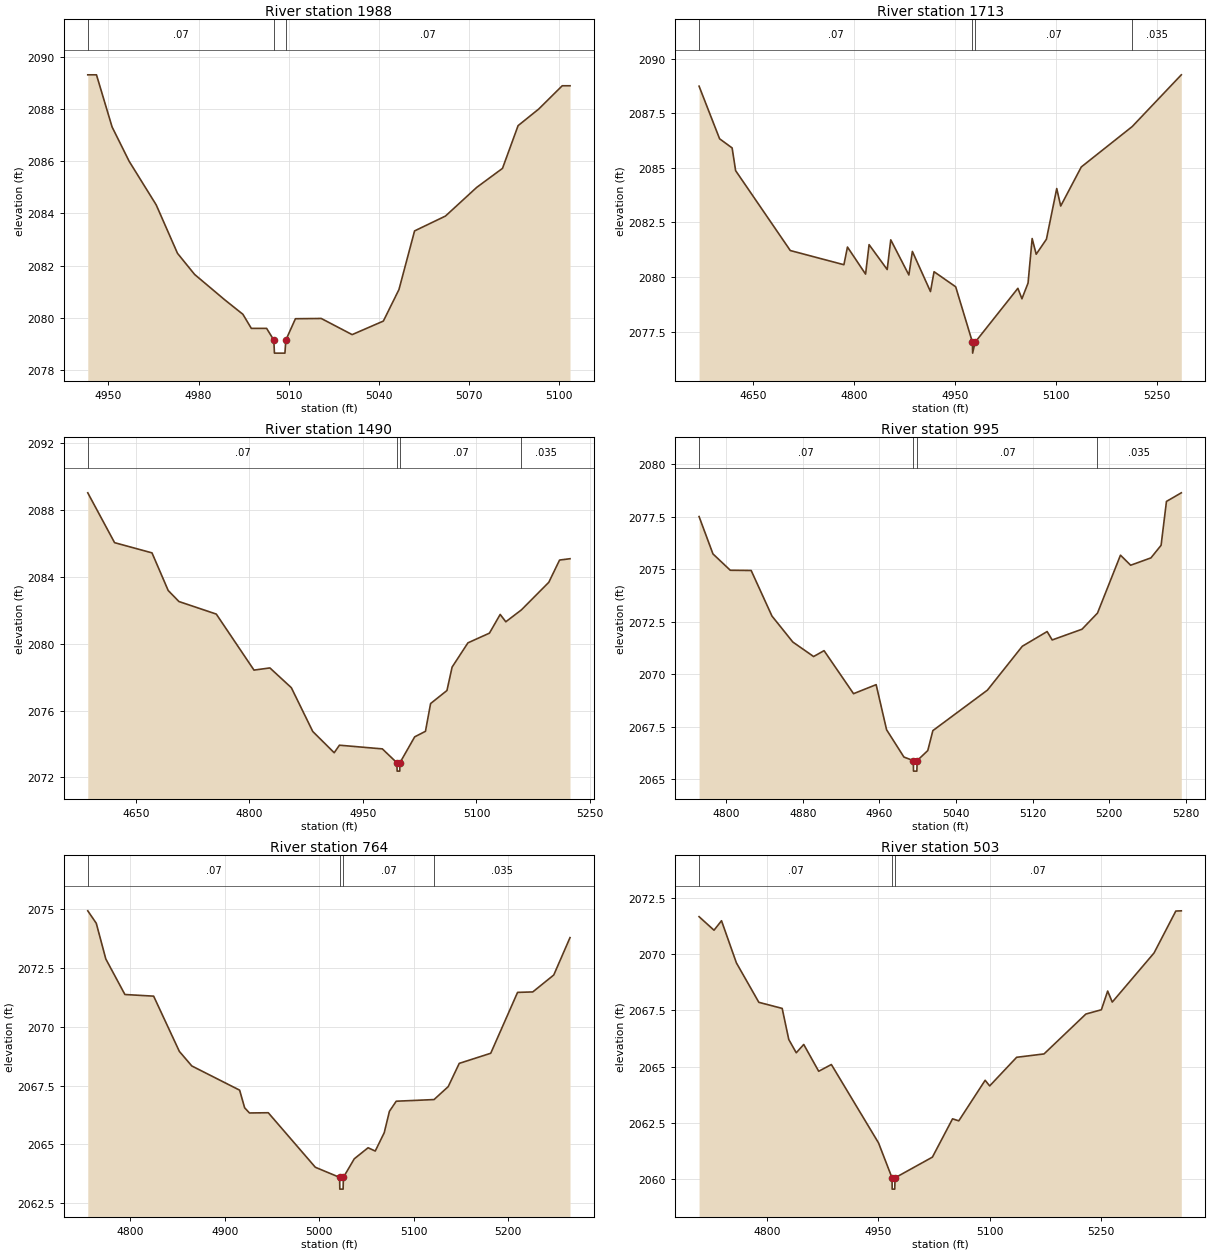
Type RM Length L Ch R = 1,1988,275,275,275
BEGIN DESCRIPTION:
Sweetwater Creek Trib 27 T11_1T 3.0
END DESCRIPTION:
XS GIS Cut Line= 3
      1388455.02      6873288.01      1388405.12      6873260.67
      1388304.99      6873288.00
#Sta/Elev= 29
  4943.1 2089.32  4946.0 2089.32  4951.2 2087.32  4956.9 2086.00  4965.9 2084.33
  4973.0 2082.47  4978.7 2081.66  4988.7 2080.69  4994.8 2080.13  4997.6 2079.59
  5000.0 2079.59  5002.7 2079.59  5005.1 2079.14  5005.3 2078.64  5008.8 2078.64
  5009.1 2079.14  5012.3 2079.96  5020.9 2079.97  5031.2 2079.35  5041.6 2079.87
  5046.8 2081.08  5052.0 2083.33  5062.3 2083.90  5072.7 2085.00  5081.3 2085.73
  5086.5 2087.37  5093.4 2088.01  5101.2 2088.90  5103.8 2088.90
#Mann=3,-1,0
  4943.1    0.07       0  5005.1    0.07       0  5009.1    0.07       0
Bank Sta=5005.1,5009.1
Exp/Cntr=0.3,0.1

Type RM Length L Ch R = 1,1713,223,223,223
BEGIN DESCRIPTION:
Sweetwater Creek Trib 27 T11_1T 4384
END DESCRIPTION:
XS GIS Cut Line= 3
      1388664.05      6872927.17      1388254.80      6873058.14
      1388101.95      6873300.46
#Sta/Elev= 30
  4570.3 2088.74  4600.8 2086.33  4619.4 2085.91  4624.6 2084.87  4705.8 2081.21
  4785.4 2080.56  4790.7 2081.37  4817.6 2080.13  4822.8 2081.48  4849.7 2080.34
  4855.0 2081.70  4881.9 2080.09  4887.1 2081.17  4914.0 2079.33  4919.3 2080.24
  4951.4 2079.55  4976.3 2077.01  4976.6 2076.51  4980.3 2077.01  5043.8 2079.48
  5049.8 2079.00  5058.9 2079.72  5065.0 2081.76  5071.0 2081.04  5086.2 2081.73
  5101.5 2084.05  5107.4 2083.25  5138.0 2085.04  5213.6 2086.89  5286.5 2089.26
#Mann=4,-1,0
  4570.3    0.07       0  4976.3    0.07       0  4980.3    0.07       0
  5213.6   0.035       0
Bank Sta=4976.3,4980.3
Exp/Cntr=0.3,0.1

Type RM Length L Ch R = 1,1490,495,495,495
BEGIN DESCRIPTION:
Sweetwater Creek Trib 27 T11_1T 2.0
END DESCRIPTION:
XS GIS Cut Line= 3
      1388455.03      6872587.97      1388155.53      6872872.78
      1388005.01      6873037.99
#Sta/Elev= 30
  4586.7 2089.02  4622.1 2086.04  4671.5 2085.43  4692.9 2083.18  4707.1 2082.52
  4756.4 2081.77  4806.2 2078.42  4827.2 2078.55  4855.5 2077.37  4883.8 2074.75
  4912.1 2073.48  4919.0 2073.93  4975.7 2073.71  4994.9 2072.88  4995.2 2072.38
  4998.7 2072.38  4998.9 2072.88  5018.4 2074.43  5032.6 2074.76  5039.4 2076.42
  5061.0 2077.20  5067.8 2078.60  5088.7 2080.05  5117.1 2080.63  5131.3 2081.75
  5138.7 2081.31  5159.3 2082.02  5195.5 2083.67  5209.7 2085.00  5223.5 2085.08
#Mann=4,-1,0
  4586.7    0.07       0  4994.9    0.07       0  4998.9    0.07       0
  5159.3   0.035       0
Bank Sta=4994.9,4998.9
Exp/Cntr=0.3,0.1

Type RM Length L Ch R = 1,995,231,231,231
BEGIN DESCRIPTION:
Sweetwater Creek Trib 27 T11_1T 1.0
END DESCRIPTION:
XS GIS Cut Line= 3
      1388104.97      6872388.01      1387895.13      6872477.95
      1387805.01      6872737.97
#Sta/Elev= 30
  4771.7 2077.51  4786.2 2075.73  4804.3 2074.95  4826.1 2074.94  4847.8 2072.77
  4869.6 2071.53  4891.3 2070.84  4902.2 2071.12  4933.0 2069.07  4956.6 2069.50
  4967.5 2067.35  4985.6 2066.05  4995.4 2065.88  4995.6 2065.38  4999.1 2065.38
  4999.4 2065.88  5010.5 2066.36  5015.8 2067.31  5072.8 2069.24  5109.2 2071.33
  5135.1 2072.03  5140.4 2071.63  5171.5 2072.14  5187.7 2072.91  5211.7 2075.67
  5222.3 2075.19  5243.5 2075.54  5254.1 2076.14  5259.7 2078.23  5275.2 2078.64
#Mann=4,-1,0
  4771.7    0.07       0  4995.4    0.07       0  4999.4    0.07       0
  5187.7   0.035       0
Bank Sta=4995.4,4999.4
Exp/Cntr=0.3,0.1

Type RM Length L Ch R = 1,764,261,261,261
BEGIN DESCRIPTION:
Sweetwater Creek Trib 27 T11_1T 4383
END DESCRIPTION:
XS GIS Cut Line= 3
      1387973.90      6872278.31      1387731.61      6872314.69
      1387616.05      6872553.50
#Sta/Elev= 30
  4755.0 2074.94  4764.0 2074.41  4774.1 2072.89  4794.3 2071.38  4824.7 2071.31
  4851.9 2068.96  4865.1 2068.34  4915.7 2067.31  4921.0 2066.56  4926.1 2066.34
  4946.0 2066.35  4995.8 2064.03  5021.5 2063.60  5021.7 2063.10  5025.2 2063.10
  5025.5 2063.60  5037.0 2064.39  5051.6 2064.86  5059.2 2064.72  5068.7 2065.50
  5074.2 2066.41  5081.4 2066.84  5121.4 2066.91  5136.4 2067.46  5148.1 2068.45
  5181.4 2068.88  5209.8 2071.47  5225.9 2071.49  5248.1 2072.21  5265.3 2073.80
#Mann=4,-1,0
  4755.0    0.07       0  5021.5    0.07       0  5025.5    0.07       0
  5121.4   0.035       0
Bank Sta=5021.5,5025.5
Exp/Cntr=0.3,0.1

Type RM Length L Ch R = 1,503,185,185,185
BEGIN DESCRIPTION:
Sweetwater Creek Trib 27 T11_1T 2910
END DESCRIPTION:
XS GIS Cut Line= 3
      1387904.96      6872137.99      1387615.58      6872097.52
      1387404.99      6872388.02
#Sta/Elev= 30
  4707.8 2071.66  4728.0 2071.06  4738.1 2071.48  4758.2 2069.61  4788.5 2067.86
  4820.0 2067.59  4828.9 2066.21  4839.0 2065.62  4849.1 2065.99  4869.3 2064.80
  4886.4 2065.10  4950.1 2061.62  4968.3 2060.07  4968.5 2059.57  4972.0 2059.57
  4972.3 2060.07  5022.8 2060.99  5050.0 2062.69  5058.4 2062.60  5094.0 2064.40
  5100.1 2064.15  5136.5 2065.42  5173.5 2065.57  5230.0 2067.34  5250.9 2067.53
  5259.4 2068.36  5265.6 2067.87  5322.0 2070.05  5351.4 2071.91  5358.8 2071.92
#Mann=3,-1,0
  4707.8    0.07       0  4968.3    0.07       0  4972.3    0.07       0
Bank Sta=4968.3,4972.3
Exp/Cntr=0.3,0.1

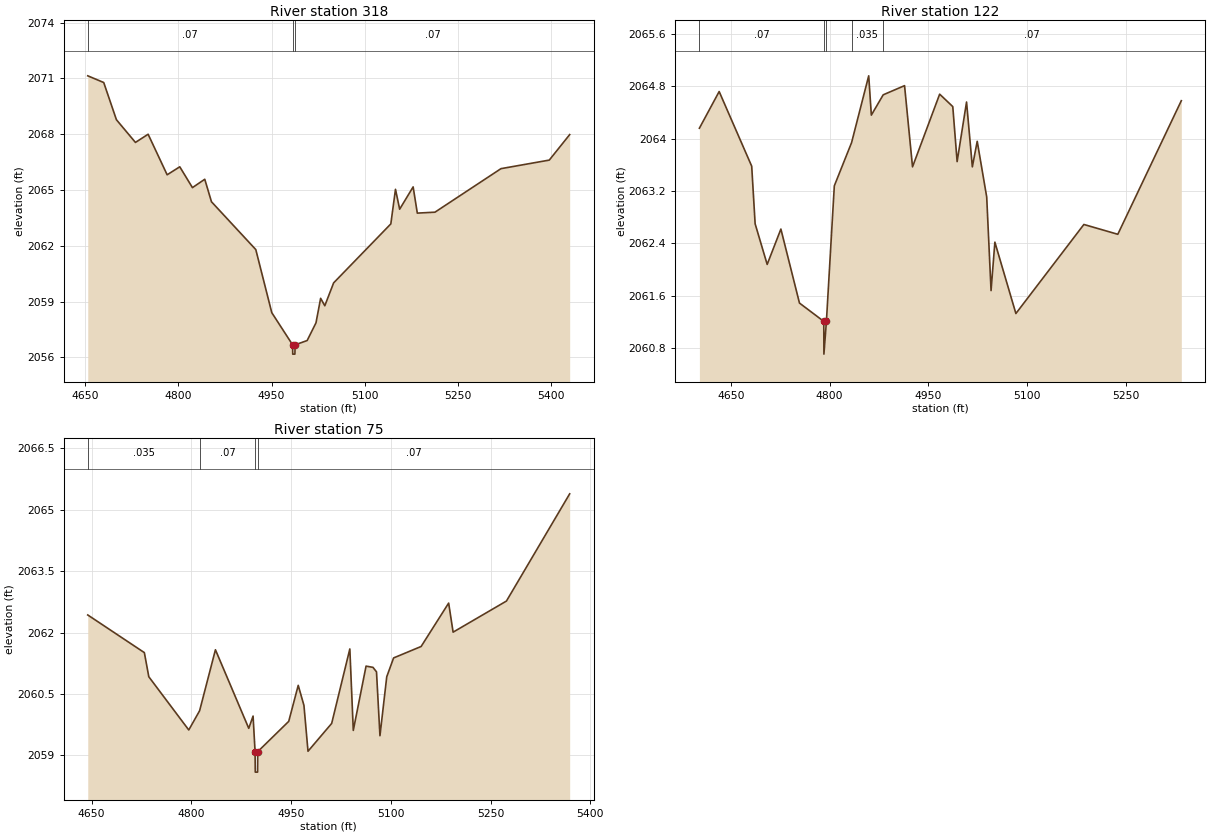
Type RM Length L Ch R = 1,318,196,196,196
BEGIN DESCRIPTION:
Sweetwater Creek Trib 27 T11_1T 4387
END DESCRIPTION:
XS GIS Cut Line= 3
      1387950.25      6872010.21      1387611.06      6871943.45
      1387324.67      6872263.53
#Sta/Elev= 30
  4654.3 2071.14  4680.0 2070.78  4700.4 2068.78  4731.0 2067.56  4751.4 2068.00
  4782.0 2065.82  4802.3 2066.25  4822.7 2065.13  4842.5 2065.58  4853.3 2064.37
  4924.6 2061.80  4950.3 2058.41  4983.8 2056.68  4984.0 2056.18  4987.5 2056.18
  4987.8 2056.68  5007.2 2056.91  5021.4 2057.86  5028.9 2059.18  5035.6 2058.78
  5049.8 2060.01  5141.8 2063.18  5149.3 2065.04  5156.0 2063.97  5177.7 2065.17
  5184.4 2063.76  5212.8 2063.81  5319.0 2066.15  5396.7 2066.61  5429.5 2067.98
#Mann=3,-1,0
  4654.3    0.07       0  4983.8    0.07       0  4987.8    0.07       0
Bank Sta=4983.8,4987.8
Exp/Cntr=0.3,0.1

Type RM Length L Ch R = 1,122,47,47,47
BEGIN DESCRIPTION:
Sweetwater Creek Trib 27 T11_1T 4386
END DESCRIPTION:
XS GIS Cut Line= 6
      1387843.87      6871875.65      1387644.24      6871818.15
      1387604.09      6871781.26      1387452.18      6871813.81
      1387428.31      6871853.96      1387380.91      6872114.77
#Sta/Elev= 30
  4602.3 2064.16  4632.3 2064.72  4681.7 2063.58  4686.9 2062.70  4705.2 2062.08
  4726.0 2062.62  4754.2 2061.49  4791.1 2061.21  4791.3 2060.71  4795.1 2061.21
  4807.1 2063.28  4833.3 2063.94  4859.3 2064.96  4863.3 2064.36  4881.3 2064.67
  4913.7 2064.81  4925.8 2063.57  4967.0 2064.68  4986.9 2064.49  4993.5 2063.65
  5007.8 2064.56  5016.6 2063.57  5024.0 2063.96  5038.4 2063.11  5045.0 2061.68
  5050.8 2062.42  5082.7 2061.33  5185.9 2062.69  5237.4 2062.54  5333.8 2064.58
#Mann=5,-1,0
  4602.3    0.07       0  4791.1    0.07       0  4795.1    0.07       0
  4833.3   0.035       0  4881.3    0.07       0
Bank Sta=4791.1,4795.1
Exp/Cntr=0.3,0.1

Type RM Length L Ch R = 1,75,0,0,0
BEGIN DESCRIPTION:
Sweetwater Creek Trib 27 T11_1T 4385
END DESCRIPTION:
XS GIS Cut Line= 4
      1387776.62      6871778.00      1387469.54      6871759.56
      1387430.25      6871787.41      1387335.23      6872143.86
#Sta/Elev= 30
  4644.2 2062.43  4729.3 2061.51  4736.0 2060.92  4796.1 2059.62  4812.4 2060.09
  4836.2 2061.58  4886.3 2059.66  4892.8 2059.96  4895.8 2059.09  4896.1 2058.59
  4899.6 2058.59  4899.8 2059.09  4946.4 2059.83  4960.7 2060.71  4969.3 2060.22
  4975.4 2059.10  5011.0 2059.78  5038.3 2061.60  5043.5 2059.61  5062.7 2061.18
  5073.1 2061.15  5078.4 2061.04  5083.6 2059.48  5093.8 2060.92  5104.1 2061.38
  5145.5 2061.66  5186.9 2062.72  5193.6 2062.01  5273.8 2062.77  5368.9 2065.39
#Mann=4,-1,0
  4644.2   0.035       0  4812.4    0.07       0  4895.8    0.07       0
  4899.8    0.07       0
Bank Sta=4895.8,4899.8
Exp/Cntr=0.3,0.1

Chan Stop Cuts=-1