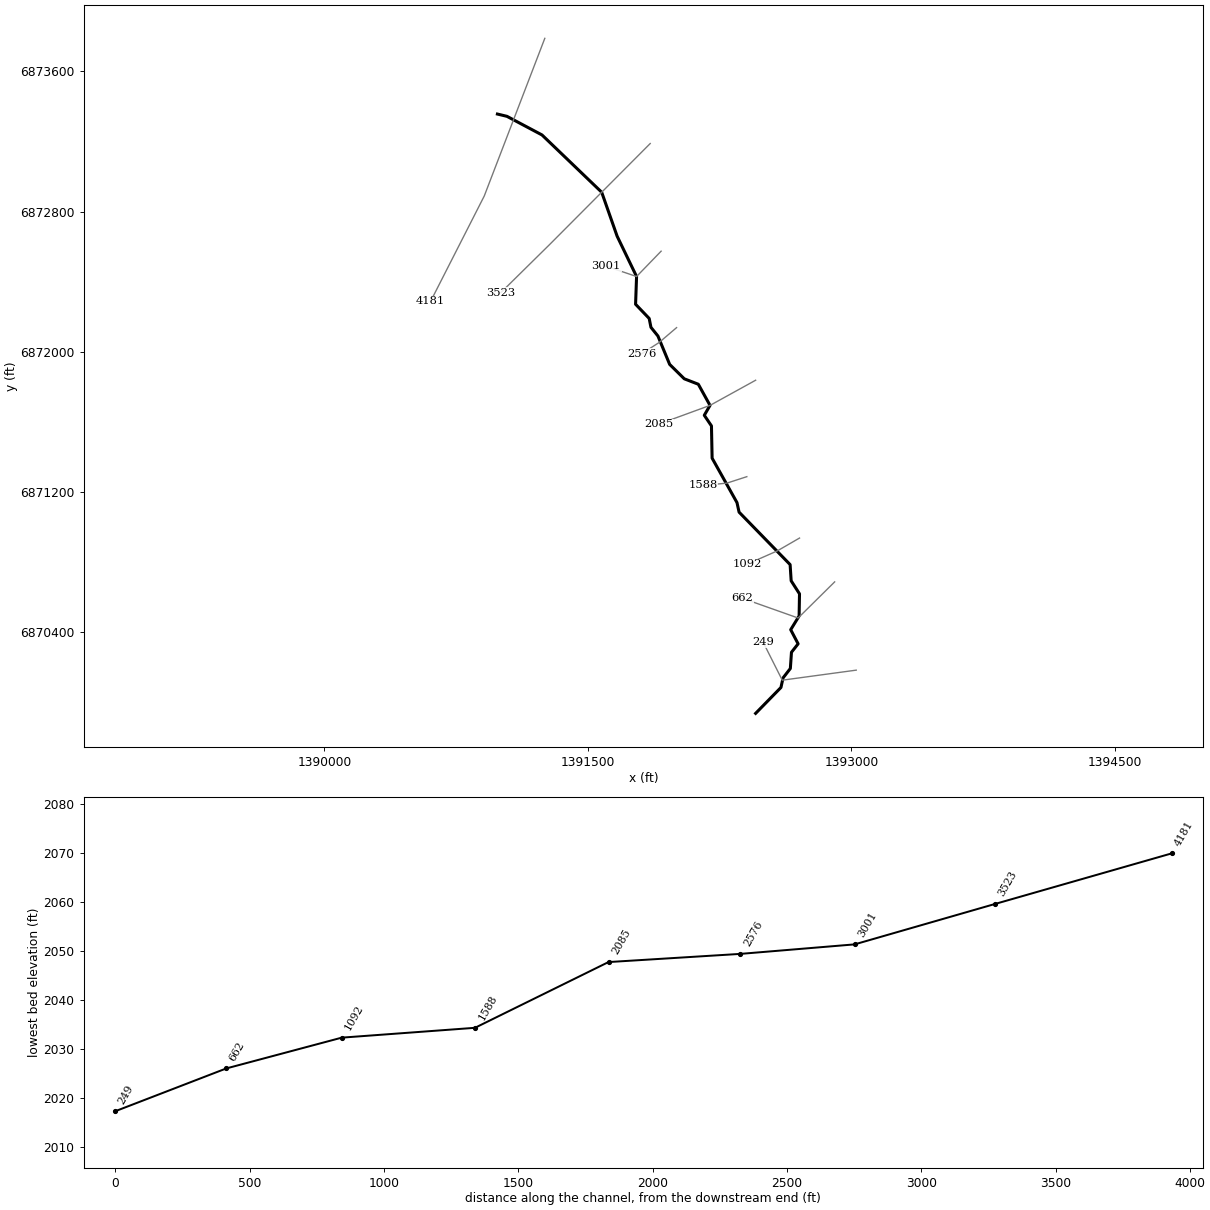
--- Sweetwater Creek Trib 27 T12.prj (project) ---

Proj Title=Sweetwater Creek Trib 27 T12 Base Level Engineering
Current Plan=p01
Default Exp/Contr=0.3,0.1
English Units
Geom File=g01
Flow File=f01
Plan File=p01
BEGIN DESCRIPTION:
Sweetwater Creek Trib 27 T12
END DESCRIPTION:

--- Sweetwater Creek Trib 27 T12.p01 (plan) ---

Plan Title=Multiple Run
Short Identifier=Multiple
Geom File=g01
Flow File=f01
Subcritical Flow
K Sum by GR= 0
Std Step Tol= 0.01
Critical Tol= 0.01
Num of Std Step Trials= 20
Max Error Tol= 0.3
Flow Tol Ratio= 0.001
Split Flow NTrial= 30
Split Flow Tol= 0.02
Split Flow Ratio= 0.02
Log Output Level= 0
Friction Slope Method= 1
Unsteady Friction Slope Method= 2
Unsteady Bridges Friction Slope Method= 1
Parabolic Critical Depth
Global Vel Dist=  1 , 1 , 1
Global Log Level= 0
CheckData=True
Encroach Param= -1, 0, 0, 0
BEGIN DESCRIPTION:
Multiple Run
END DESCRIPTION:

--- Sweetwater Creek Trib 27 T12.f01 (steady flow) ---

Flow Title=Multiple
Number of Profiles=7
Profile Names=10-year,25-year,50-year,1pct_min,100-year,1pct_plu,500-year
River Rch & RM= Sweetwater Creek,Reach-1,4181
     187     258     317     194     388     773     585
Boundary for River Rch & Prof#=Sweetwater Creek,Reach-1,1
Up Type=0
Dn Type=3
Dn Slope=0.005
Boundary for River Rch & Prof#=Sweetwater Creek,Reach-1,2
Up Type=0
Dn Type=3
Dn Slope=0.005
Boundary for River Rch & Prof#=Sweetwater Creek,Reach-1,3
Up Type=0
Dn Type=3
Dn Slope=0.005
Boundary for River Rch & Prof#=Sweetwater Creek,Reach-1,4
Up Type=0
Dn Type=3
Dn Slope=0.005
Boundary for River Rch & Prof#=Sweetwater Creek,Reach-1,5
Up Type=0
Dn Type=3
Dn Slope=0.005
Boundary for River Rch & Prof#=Sweetwater Creek,Reach-1,6
Up Type=0
Dn Type=3
Dn Slope=0.005
Boundary for River Rch & Prof#=Sweetwater Creek,Reach-1,7
Up Type=0
Dn Type=3
Dn Slope=0.005

--- Sweetwater Creek Trib 27 T12.g01 (geometry) ---

Geom Title=Existing Conditions

River Reach=Sweetwater Creek,Reach-1
Reach XY= 30
      1390985.22      6873356.17      1391039.47      6873343.15
      1391239.12      6873236.82      1391578.82      6872910.19
      1391666.64      6872659.56      1391777.32      6872429.53
      1391771.71      6872271.36      1391849.17      6872190.31
      1391859.19      6872139.74      1391898.92      6872090.20
      1391965.76      6871928.30      1392048.95      6871846.16
      1392128.85      6871815.14      1392195.42      6871694.55
      1392162.80      6871638.10      1392203.62      6871577.57
      1392207.35      6871393.52      1392348.90      6871140.19
      1392360.83      6871085.70      1392651.39      6870786.50
      1392657.36      6870693.98      1392704.81      6870619.72
      1392702.61      6870493.52      1392654.70      6870415.16
      1392696.90      6870334.71      1392659.09      6870286.50
      1392652.67      6870193.97      1392611.14      6870140.17
      1392599.17      6870085.70      1392455.00      6869938.00

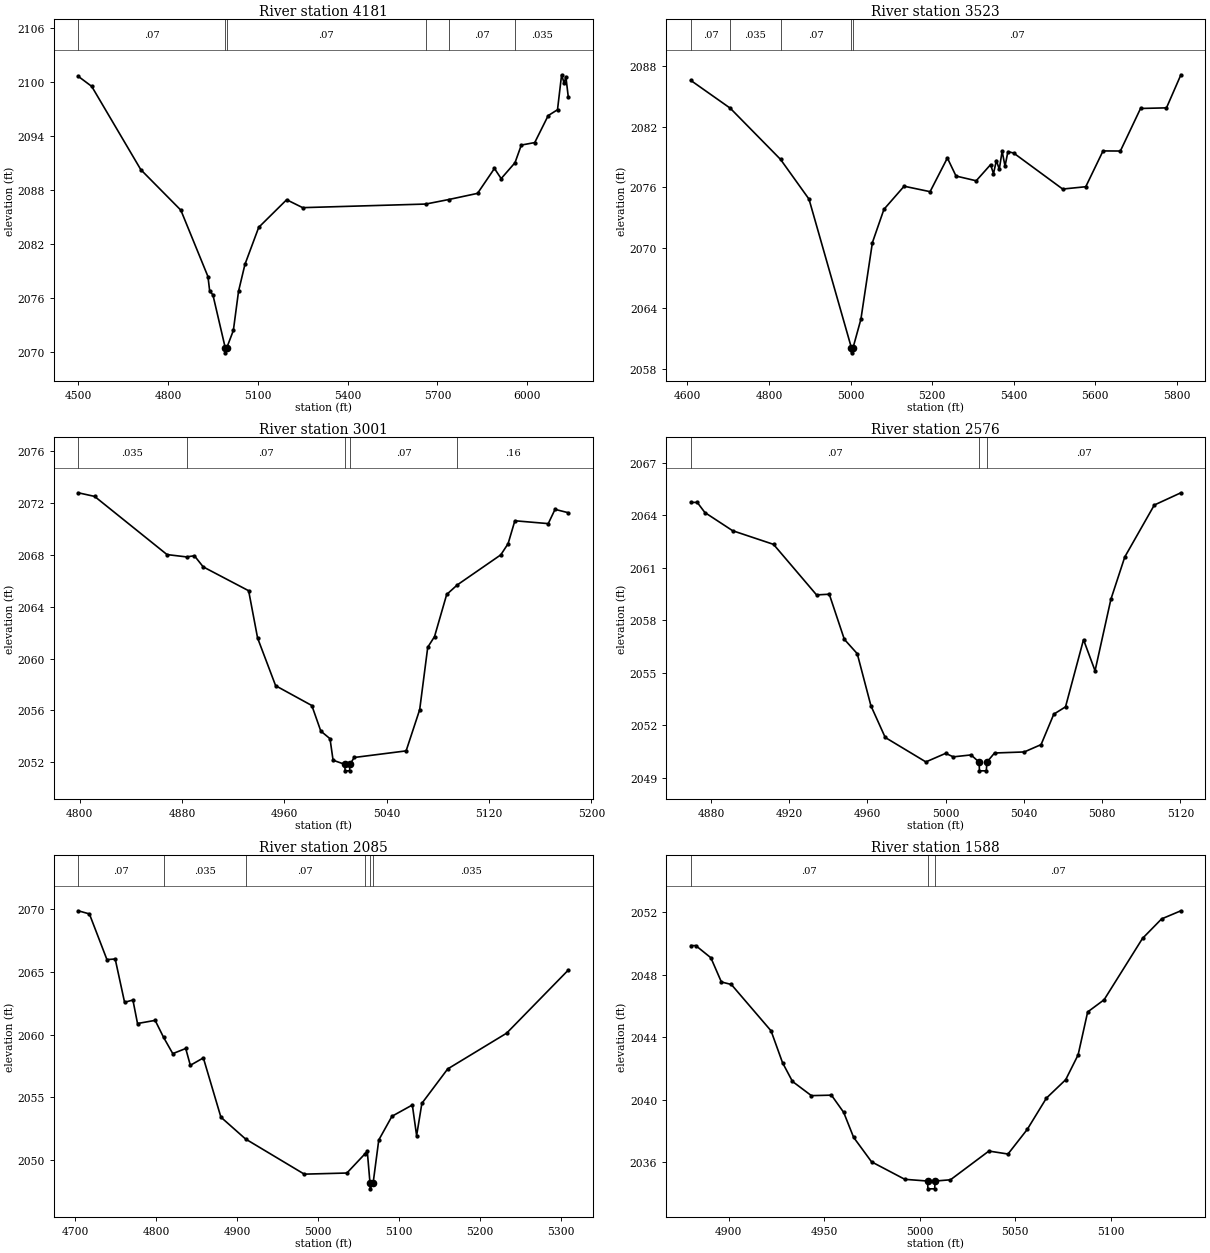
Type RM Length L Ch R = 1,4181,658,658,658
BEGIN DESCRIPTION:
Sweetwater Creek Trib 27 T12 7.0
END DESCRIPTION:
XS GIS Cut Line= 3
      1391254.98      6873787.96      1390910.22      6872888.53
      1390604.99      6872287.98
#Sta/Elev= 30
  4500.3 2100.66  4545.3 2099.54  4709.4 2090.27  4843.0 2085.77  4933.6 2078.38
  4939.3 2076.78  4950.1 2076.35  4991.7 2070.40  4992.0 2069.90  4995.7 2070.40
  5018.4 2072.39  5035.7 2076.75  5057.1 2079.74  5103.1 2083.86  5196.4 2086.93
  5249.9 2086.05  5661.0 2086.45  5737.3 2086.95  5834.0 2087.64  5890.4 2090.41
  5912.8 2089.28  5959.1 2091.05  5980.1 2093.01  6025.0 2093.29  6069.9 2096.29
  6101.0 2096.94  6114.7 2100.83  6123.3 2099.88  6128.9 2100.63  6137.2 2098.31
#Mann=6,-1,0
  4500.3    0.07       0  4991.7    0.07       0  4995.7    0.07       0
  5661.0   0.035       0  5737.3    0.07       0  5959.1   0.035       0
Bank Sta=4991.7,4995.7
Exp/Cntr=0.3,0.1

Type RM Length L Ch R = 1,3523,522,522,522
BEGIN DESCRIPTION:
Sweetwater Creek Trib 27 T12 6.0
END DESCRIPTION:
XS GIS Cut Line= 3
      1391854.98      6873187.98      1391281.73      6872611.36
      1391004.97      6872337.97
#Sta/Elev= 30
  4608.3 2086.58  4704.9 2083.83  4828.4 2078.75  4898.2 2074.81  5002.2 2060.07
  5002.5 2059.57  5006.2 2060.07  5025.5 2062.90  5053.7 2070.50  5082.0 2073.80
  5131.5 2076.09  5195.2 2075.55  5237.6 2078.89  5258.8 2077.10  5308.3 2076.63
  5343.6 2078.23  5350.7 2077.33  5357.8 2078.64  5364.9 2077.77  5371.9 2079.56
  5379.0 2078.08  5386.1 2079.52  5400.2 2079.38  5520.4 2075.81  5577.0 2076.04
  5619.4 2079.59  5661.9 2079.58  5711.4 2083.80  5775.0 2083.86  5810.4 2087.14
#Mann=5,-1,0
  4608.3    0.07       0  4704.9   0.035       0  4828.4    0.07       0
  5002.2    0.07       0  5006.2    0.07       0
Bank Sta=5002.2,5006.2
Exp/Cntr=0.3,0.1

Type RM Length L Ch R = 1,3001,425,425,425
BEGIN DESCRIPTION:
Sweetwater Creek Trib 27 T12 5.0
END DESCRIPTION:
XS GIS Cut Line= 3
      1391917.11      6872574.09      1391777.32      6872429.53
      1391604.97      6872488.01
#Sta/Elev= 30
  4798.9 2072.79  4811.7 2072.51  4868.3 2068.02  4883.6 2067.84  4889.7 2067.93
  4896.6 2067.07  4932.1 2065.23  4939.1 2061.58  4953.2 2057.90  4981.5 2056.37
  4988.5 2054.40  4995.7 2053.81  4998.1 2052.15  5007.3 2051.83  5007.5 2051.33
  5011.0 2051.33  5011.3 2051.83  5014.6 2052.36  5055.2 2052.87  5065.8 2056.05
  5072.1 2060.87  5077.4 2061.69  5086.9 2064.94  5095.2 2065.68  5129.2 2068.00
  5134.9 2068.86  5140.2 2070.63  5166.3 2070.41  5171.6 2071.51  5182.0 2071.25
#Mann=5,-1,0
  4798.9   0.035       0  4883.6    0.07       0  5007.3    0.07       0
  5011.3    0.07       0  5095.2    0.16       0
Bank Sta=5007.3,5011.3
Exp/Cntr=0.3,0.1

Type RM Length L Ch R = 1,2576,491,491,491
BEGIN DESCRIPTION:
Sweetwater Creek Trib 27 T12 4.0
END DESCRIPTION:
XS GIS Cut Line= 3
      1392005.02      6872138.02      1391905.94      6872053.39
      1391804.98      6871987.98
#Sta/Elev= 30
  4869.7 2064.74  4873.0 2064.74  4876.9 2064.16  4891.1 2063.12  4912.0 2062.34
  4934.0 2059.45  4940.5 2059.49  4948.2 2056.91  4954.8 2056.09  4961.8 2053.11
  4969.1 2051.30  4989.9 2049.90  5000.0 2050.39  5003.9 2050.19  5013.0 2050.30
  5017.1 2049.89  5017.3 2049.39  5020.8 2049.39  5021.1 2049.89  5025.0 2050.41
  5040.2 2050.47  5048.8 2050.89  5055.3 2052.63  5061.3 2053.05  5070.5 2056.89
  5076.4 2055.11  5084.5 2059.20  5091.6 2061.62  5106.7 2064.59  5120.3 2065.29
#Mann=3,-1,0
  4869.7    0.07       0  5017.1    0.07       0  5021.1    0.07       0
Bank Sta=5017.1,5021.1
Exp/Cntr=0.3,0.1

Type RM Length L Ch R = 1,2085,497,497,497
BEGIN DESCRIPTION:
Sweetwater Creek Trib 27 T12 3.0
END DESCRIPTION:
XS GIS Cut Line= 3
      1392455.02      6871838.01      1392195.42      6871694.55
      1391904.95      6871587.98
#Sta/Elev= 30
  4703.4 2069.87  4717.2 2069.62  4738.9 2065.98  4749.1 2066.03  4760.7 2062.58
  4771.0 2062.76  4776.7 2060.89  4798.5 2061.14  4808.9 2059.79  4820.3 2058.49
  4836.3 2058.90  4842.0 2057.56  4858.1 2058.15  4879.8 2053.43  4910.3 2051.69
  4982.9 2048.89  5035.6 2048.98  5057.8 2050.50  5060.8 2050.72  5064.1 2048.22
  5064.4 2047.72  5068.1 2048.22  5075.0 2051.61  5091.3 2053.50  5116.5 2054.40
  5121.8 2051.96  5128.3 2054.53  5160.2 2057.27  5233.1 2060.12  5309.4 2065.15
#Mann=6,-1,0
  4703.4    0.07       0  4808.9   0.035       0  4910.3    0.07       0
  5057.8   0.035       0  5064.1    0.07       0  5068.1   0.035       0
Bank Sta=5064.1,5068.1
Exp/Cntr=0.3,0.1

Type RM Length L Ch R = 1,1588,496,496,496
BEGIN DESCRIPTION:
Sweetwater Creek Trib 27 T12 2.0
END DESCRIPTION:
XS GIS Cut Line= 3
      1392404.99      6871288.00      1392291.03      6871251.07
      1392154.95      6871238.00
#Sta/Elev= 30
  4880.2 2049.88  4882.8 2049.88  4890.7 2049.10  4896.2 2047.55  4901.4 2047.39
  4922.2 2044.42  4928.2 2042.38  4933.4 2041.18  4943.3 2040.27  4953.8 2040.30
  4960.2 2039.20  4965.4 2037.60  4974.8 2036.03  4992.2 2034.91  5004.1 2034.80
  5004.3 2034.30  5007.8 2034.30  5008.1 2034.80  5016.1 2034.88  5036.2 2036.72
  5046.2 2036.53  5056.3 2038.11  5066.3 2040.11  5076.4 2041.29  5082.9 2042.88
  5087.9 2045.63  5096.5 2046.41  5116.6 2050.34  5126.6 2051.59  5136.7 2052.11
#Mann=3,-1,0
  4880.2    0.07       0  5004.1    0.07       0  5008.1    0.07       0
Bank Sta=5004.1,5008.1
Exp/Cntr=0.3,0.1

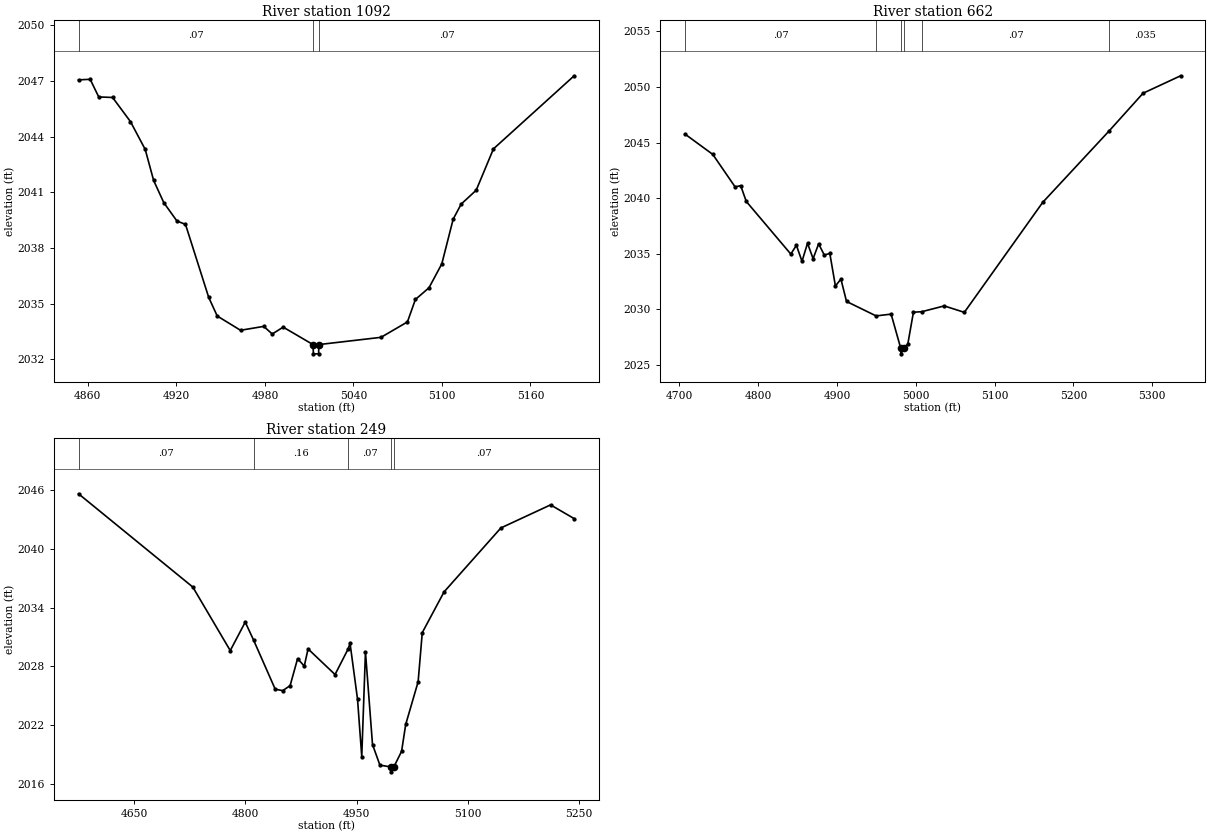
Type RM Length L Ch R = 1,1092,430,430,430
BEGIN DESCRIPTION:
Sweetwater Creek Trib 27 T12 1.0
END DESCRIPTION:
XS GIS Cut Line= 3
      1392705.00      6870938.00      1392578.39      6870864.69
      1392404.99      6870788.00
#Sta/Elev= 30
  4853.7 2047.06  4861.6 2047.09  4867.4 2046.14  4876.8 2046.11  4888.9 2044.81
  4898.9 2043.31  4904.6 2041.64  4911.5 2040.44  4920.4 2039.45  4926.2 2039.27
  4941.9 2035.34  4947.7 2034.33  4963.5 2033.56  4979.2 2033.77  4985.0 2033.36
  4992.4 2033.73  5012.6 2032.79  5012.9 2032.29  5016.4 2032.29  5016.6 2032.79
  5058.7 2033.18  5076.6 2034.01  5082.0 2035.22  5091.2 2035.85  5099.9 2037.14
  5107.6 2039.55  5113.0 2040.36  5123.2 2041.11  5134.9 2043.34  5189.6 2047.28
#Mann=3,-1,0
  4853.7    0.07       0  5012.6    0.07       0  5016.6    0.07       0
Bank Sta=5012.6,5016.6
Exp/Cntr=0.3,0.1

Type RM Length L Ch R = 1,662,413,413,413
BEGIN DESCRIPTION:
Sweetwater Creek Trib 27 T12 2894
END DESCRIPTION:
XS GIS Cut Line= 3
      1392904.98      6870687.98      1392696.82      6870481.93
      1392380.08      6870594.36
#Sta/Elev= 30
  4707.1 2045.76  4742.4 2043.93  4770.7 2041.01  4777.8 2041.12  4784.9 2039.70
  4841.4 2034.97  4848.5 2035.76  4855.6 2034.32  4862.6 2035.94  4869.7 2034.56
  4876.7 2035.89  4883.9 2034.88  4890.9 2035.03  4898.0 2032.10  4905.0 2032.72
  4912.1 2030.71  4949.6 2029.41  4968.7 2029.57  4980.9 2026.50  4981.1 2026.00
  4984.9 2026.50  4989.9 2026.89  4997.0 2029.74  5007.7 2029.79  5036.1 2030.31
  5061.6 2029.73  5161.1 2039.62  5245.6 2046.06  5288.4 2049.43  5336.1 2051.00
#Mann=6,-1,0
  4707.1    0.07       0  4949.6    0.16       0  4980.9    0.07       0
  4984.9    0.16       0  5007.7    0.07       0  5245.6   0.035       0
Bank Sta=4980.9,4984.9
Exp/Cntr=0.3,0.1

Type RM Length L Ch R = 1,249,0,0,0
BEGIN DESCRIPTION:
Sweetwater Creek Trib 27 T12 4105
END DESCRIPTION:
XS GIS Cut Line= 3
      1393027.74      6870184.57      1392606.72      6870127.29
      1392497.35      6870344.73
#Sta/Elev= 30
  4575.1 2045.59  4729.2 2036.09  4779.7 2029.62  4799.9 2032.52  4811.2 2030.68
  4840.3 2025.69  4850.4 2025.54  4860.4 2026.05  4870.5 2028.80  4879.5 2028.04
  4884.6 2029.79  4921.0 2027.18  4938.6 2029.78  4941.2 2030.37  4951.3 2024.67
  4957.0 2018.83  4962.0 2029.48  4971.5 2020.05  4981.5 2017.95  4996.3 2017.77
  4996.6 2017.27  5000.3 2017.77  5010.7 2019.36  5016.3 2022.11  5033.0 2026.44
  5038.6 2031.45  5068.0 2035.60  5144.6 2042.11  5211.6 2044.46  5243.4 2043.06
#Mann=5,-1,0
  4575.1    0.07       0  4811.2    0.16       0  4938.6    0.07       0
  4996.3    0.07       0  5000.3    0.07       0
Bank Sta=4996.3,5000.3
Exp/Cntr=0.3,0.1

Chan Stop Cuts=-1