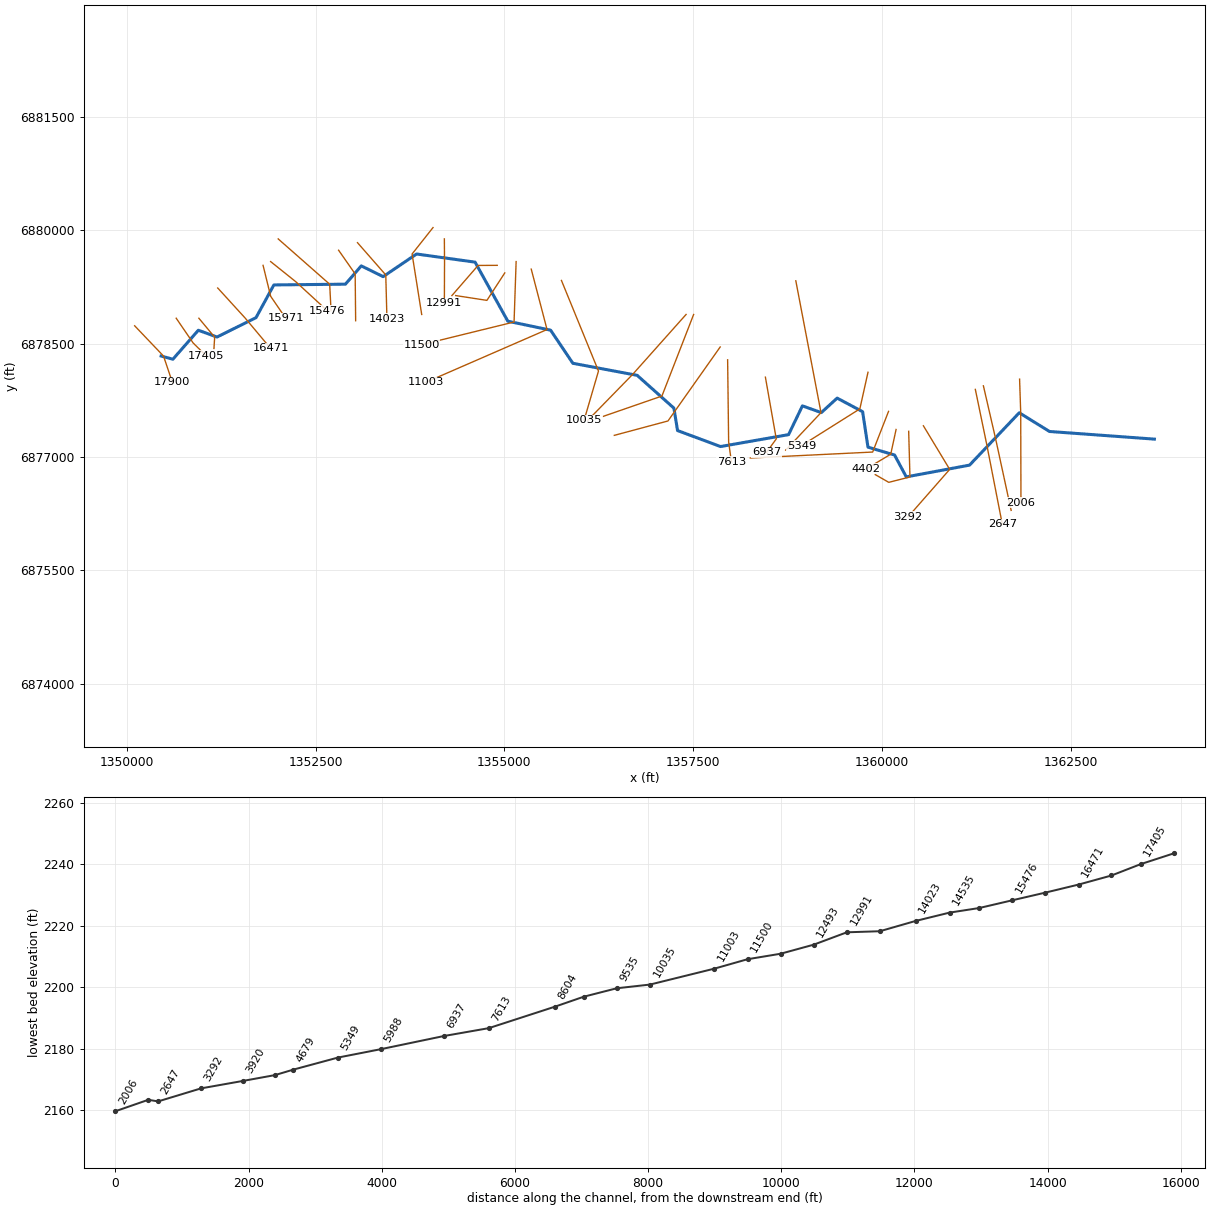
--- Sweetwater Creek Trib 27 T2.prj (project) ---

Proj Title=Sweetwater Creek Trib 27 T2 Base Level Engineering
Current Plan=p01
Default Exp/Contr=0.3,0.1
English Units
Geom File=g01
Flow File=f01
Plan File=p01
Y Axis Title=Elevation
X Axis Title(PF)=Main Channel Distance
X Axis Title(XS)=Station
BEGIN DESCRIPTION:
Sweetwater Creek Trib 27 T2
END DESCRIPTION:
DSS Export Rating Curves= 0
DSS Export Rating Curve Sorted= 0
DSS Export Volume Flow Curves= 0
DXF OffsetX= 0
DXF OffsetY= 0
DXF ScaleX= 1
DXF ScaleY= 10

--- Sweetwater Creek Trib 27 T2.p01 (plan) ---

Plan Title=Multiple Run
Short Identifier=Multiple
Geom File=g01
Flow File=f01
Subcritical Flow
K Sum by GR= 0
Std Step Tol= 0.01
Critical Tol= 0.01
Num of Std Step Trials= 20
Max Error Tol= 0.3
Flow Tol Ratio= 0.001
Split Flow NTrial= 30
Split Flow Tol= 0.02
Split Flow Ratio= 0.02
Log Output Level= 0
Friction Slope Method= 1
Unsteady Friction Slope Method= 2
Unsteady Bridges Friction Slope Method= 1
Parabolic Critical Depth
Global Vel Dist=  1 , 1 , 1
Global Log Level= 0
CheckData=True
Encroach Param= -1, 0, 0, 0
BEGIN DESCRIPTION:
Multiple Run
END DESCRIPTION:

--- Sweetwater Creek Trib 27 T2.f01 (steady flow) ---

Flow Title=Multiple
Number of Profiles=7
Profile Names=10-year,25-year,50-year,1pct_min,100-year,1pct_plu,500-year
River Rch & RM= Sweetwater Creek,Reach-1,17900
     489     729     940     602    1201    2397    1992
River Rch & RM= Sweetwater Creek,Reach-1,13487
     564     832    1066     678    1352    2698    2206
River Rch & RM= Sweetwater Creek,Reach-1,5349
     620     912    1166     739    1475    2944    2394
Boundary for River Rch & Prof#=Sweetwater Creek,Reach-1,1
Up Type=0
Dn Type=3
Dn Slope=0.005
Boundary for River Rch & Prof#=Sweetwater Creek,Reach-1,2
Up Type=0
Dn Type=3
Dn Slope=0.005
Boundary for River Rch & Prof#=Sweetwater Creek,Reach-1,3
Up Type=0
Dn Type=3
Dn Slope=0.005
Boundary for River Rch & Prof#=Sweetwater Creek,Reach-1,4
Up Type=0
Dn Type=3
Dn Slope=0.005
Boundary for River Rch & Prof#=Sweetwater Creek,Reach-1,5
Up Type=0
Dn Type=3
Dn Slope=0.005
Boundary for River Rch & Prof#=Sweetwater Creek,Reach-1,6
Up Type=0
Dn Type=3
Dn Slope=0.005
Boundary for River Rch & Prof#=Sweetwater Creek,Reach-1,7
Up Type=0
Dn Type=3
Dn Slope=0.005

--- Sweetwater Creek Trib 27 T2.g01 (geometry) ---

Geom Title=Existing Conditions

River Reach=Sweetwater Creek,Reach-1
Reach XY= 30
      1350455.00      6878338.00      1350611.06      6878295.47
      1350947.94      6878679.03      1351195.30      6878589.25
      1351711.47      6878845.70      1351948.00      6879278.84
      1352895.38      6879288.69      1353104.99      6879530.92
      1353394.71      6879388.60      1353836.71      6879688.06
      1354611.52      6879580.33      1355045.19      6878798.51
      1355611.21      6878680.19      1355906.28      6878241.52
      1356757.30      6878082.17      1357244.04      6877648.00
      1357291.70      6877351.40      1357861.12      6877139.76
      1358761.67      6877297.30      1358944.95      6877677.98
      1359195.36      6877589.09      1359404.91      6877780.71
      1359741.89      6877601.24      1359812.86      6877131.79
      1360164.81      6877027.49      1360319.94      6876738.24
      1361157.31      6876893.82      1361815.45      6877586.97
      1362215.50      6877339.22      1363605.00      6877238.00

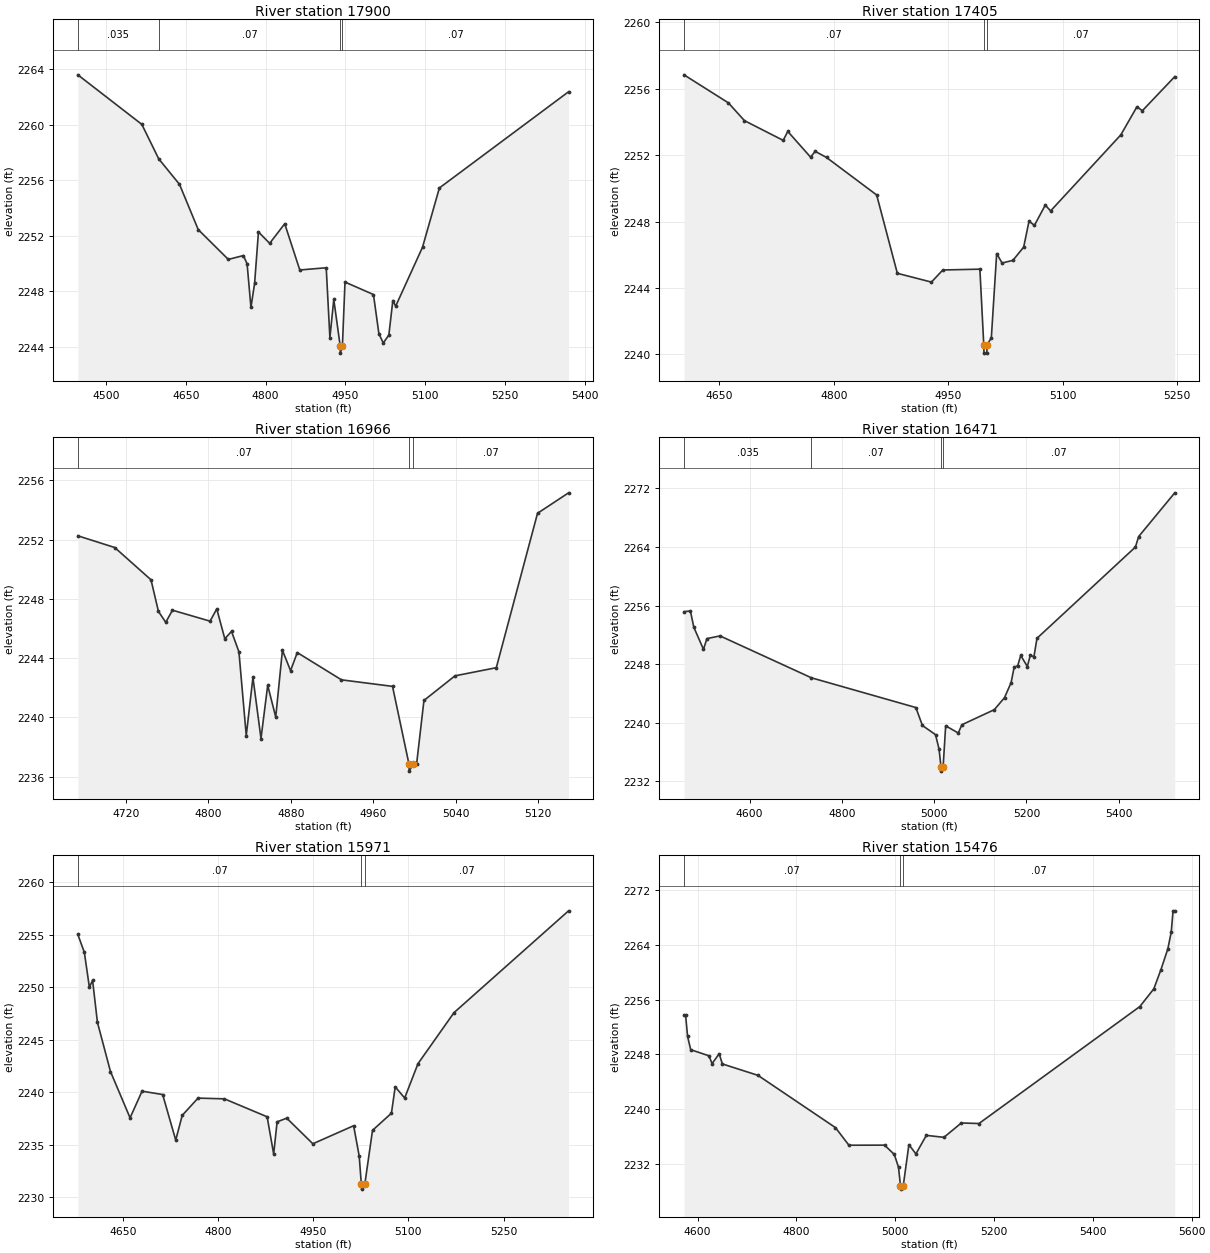
Type RM Length L Ch R = 1,17900,495,495,495
BEGIN DESCRIPTION:
Sweetwater Creek Trib 27 T2 22.0
END DESCRIPTION:
XS GIS Cut Line= 3
      1350104.98      6878738.02      1350486.81      6878337.86
      1350605.01      6877987.98
#Sta/Elev= 30
  4446.9 2263.61  4567.2 2260.04  4598.9 2257.56  4638.0 2255.72  4673.2 2252.46
  4729.8 2250.31  4758.1 2250.59  4765.1 2249.99  4772.3 2246.85  4779.2 2248.59
  4786.4 2252.29  4807.5 2251.47  4835.8 2252.88  4864.1 2249.55  4913.8 2249.71
  4920.7 2244.67  4928.0 2247.43  4940.1 2244.06  4940.3 2243.56  4944.2 2244.06
  4949.1 2248.68  5002.6 2247.78  5012.8 2244.96  5021.0 2244.29  5031.5 2244.86
  5039.0 2247.35  5044.3 2246.94  5094.8 2251.19  5126.5 2255.46  5369.3 2262.39
#Mann=4,-1,0
  4446.9   0.035       0  4598.9    0.07       0  4940.1    0.07       0
  4944.2    0.07       0
Bank Sta=4940.1,4944.2
Exp/Cntr=0.3,0.1

Type RM Length L Ch R = 1,17405,439,439,439
BEGIN DESCRIPTION:
Sweetwater Creek Trib 27 T2 21.0
END DESCRIPTION:
XS GIS Cut Line= 3
      1350655.01      6878837.99      1350878.84      6878511.07
      1351055.04      6878337.97
#Sta/Elev= 30
  4603.8 2256.84  4662.0 2255.15  4683.0 2254.08  4733.8 2252.89  4739.8 2253.43
  4769.7 2251.88  4775.7 2252.23  4790.6 2251.86  4856.3 2249.60  4883.4 2244.88
  4928.1 2244.35  4943.0 2245.08  4991.6 2245.13  4996.7 2240.57  4997.0 2240.07
  5000.7 2240.07  5000.9 2240.57  5006.6 2240.99  5013.6 2246.07  5020.7 2245.50
  5034.9 2245.66  5049.0 2246.46  5056.0 2248.02  5063.1 2247.77  5077.3 2248.99
  5084.3 2248.64  5176.3 2253.22  5197.4 2254.91  5204.6 2254.68  5247.0 2256.73
#Mann=3,-1,0
  4603.8    0.07       0  4996.7    0.07       0  5000.9    0.07       0
Bank Sta=4996.7,5000.9
Exp/Cntr=0.3,0.1

Type RM Length L Ch R = 1,16966,495,495,495
BEGIN DESCRIPTION:
Sweetwater Creek Trib 27 T2 20.0
END DESCRIPTION:
XS GIS Cut Line= 3
      1350954.97      6878838.04      1351164.14      6878587.21
      1351155.00      6878437.99
#Sta/Elev= 30
  4673.4 2252.25  4709.2 2251.46  4744.4 2249.28  4751.6 2247.15  4758.7 2246.41
  4765.2 2247.23  4801.7 2246.49  4808.2 2247.32  4816.0 2245.30  4822.5 2245.80
  4829.7 2244.42  4836.8 2238.77  4843.3 2242.69  4851.1 2238.57  4857.6 2242.16
  4865.4 2240.02  4871.9 2244.52  4879.8 2243.15  4886.3 2244.37  4929.2 2242.53
  4978.7 2242.09  4994.6 2236.87  4994.9 2236.37  4998.9 2236.87  5002.1 2236.87
  5009.2 2241.14  5039.3 2242.80  5079.4 2243.35  5119.4 2253.77  5149.5 2255.15
#Mann=3,-1,0
  4673.4    0.07       0  4994.6    0.07       0  4998.9    0.07       0
Bank Sta=4994.6,4998.9
Exp/Cntr=0.3,0.1

Type RM Length L Ch R = 1,16471,500,500,500
BEGIN DESCRIPTION:
Sweetwater Creek Trib 27 T2 19.0
END DESCRIPTION:
XS GIS Cut Line= 3
      1351205.01      6879237.99      1351570.17      6878837.60
      1351904.98      6878438.03
#Sta/Elev= 30
  4458.1 2255.17  4471.9 2255.28  4479.4 2253.04  4500.3 2250.03  4507.7 2251.50
  4536.1 2251.87  4734.1 2246.15  4960.4 2242.09  4974.6 2239.64  5003.0 2238.39
  5010.7 2236.41  5015.0 2233.91  5015.3 2233.41  5019.4 2233.91  5025.0 2239.60
  5052.3 2238.61  5060.1 2239.74  5130.4 2241.80  5152.5 2243.44  5166.8 2245.50
  5173.3 2247.58  5181.1 2247.80  5187.6 2249.21  5201.9 2247.69  5208.4 2249.23
  5216.2 2249.01  5222.8 2251.54  5436.1 2264.00  5443.1 2265.43  5521.3 2271.40
#Mann=4,-1,0
  4458.1   0.035       0  4734.1    0.07       0  5015.0    0.07       0
  5019.4    0.07       0
Bank Sta=5015,5019.4
Exp/Cntr=0.3,0.1

Type RM Length L Ch R = 1,15971,495,495,495
BEGIN DESCRIPTION:
Sweetwater Creek Trib 27 T2 18.0
END DESCRIPTION:
XS GIS Cut Line= 3
      1351805.00      6879537.98      1351905.44      6879128.73
      1352104.99      6878838.02
#Sta/Elev= 30
  4578.6 2255.05  4588.9 2253.34  4596.8 2250.03  4601.9 2250.67  4609.5 2246.68
  4630.1 2241.99  4661.0 2237.58  4679.9 2240.12  4712.4 2239.80  4733.0 2235.46
  4743.3 2237.82  4768.2 2239.46  4809.8 2239.39  4877.2 2237.68  4887.5 2234.13
  4892.9 2237.20  4908.1 2237.55  4949.3 2235.11  5013.6 2236.83  5022.4 2233.94
  5025.7 2231.29  5026.1 2230.79  5031.3 2231.29  5043.4 2236.39  5073.2 2238.02
  5079.2 2240.53  5094.1 2239.47  5115.1 2242.74  5171.9 2247.60  5352.6 2257.30
#Mann=3,-1,0
  4578.6    0.07       0  5025.7    0.07       0  5031.3    0.07       0
Bank Sta=5025.7,5031.3
Exp/Cntr=0.3,0.1

Type RM Length L Ch R = 1,15476,497,497,497
BEGIN DESCRIPTION:
Sweetwater Creek Trib 27 T2 17.0
END DESCRIPTION:
XS GIS Cut Line= 3
      1351904.99      6879588.01      1352238.52      6879320.91
      1352655.04      6878937.97
#Sta/Elev= 30
  4572.7 2253.75  4575.9 2253.75  4579.9 2250.62  4586.3 2248.68  4623.1 2247.79
  4629.5 2246.65  4643.9 2248.09  4650.3 2246.60  4722.4 2244.93  4879.2 2237.29
  4906.4 2234.72  4978.5 2234.73  4998.3 2233.37  5006.8 2231.49  5010.8 2228.80
  5011.3 2228.30  5016.4 2228.80  5027.8 2234.80  5042.0 2233.45  5063.1 2236.16
  5098.7 2235.87  5133.9 2237.97  5169.6 2237.89  5495.2 2254.99  5523.5 2257.58
  5537.7 2260.35  5551.9 2263.44  5558.7 2265.89  5562.4 2268.98  5565.8 2268.98
#Mann=3,-1,0
  4572.7    0.07       0  5010.8    0.07       0  5016.4    0.07       0
Bank Sta=5010.8,5016.4
Exp/Cntr=0.3,0.1

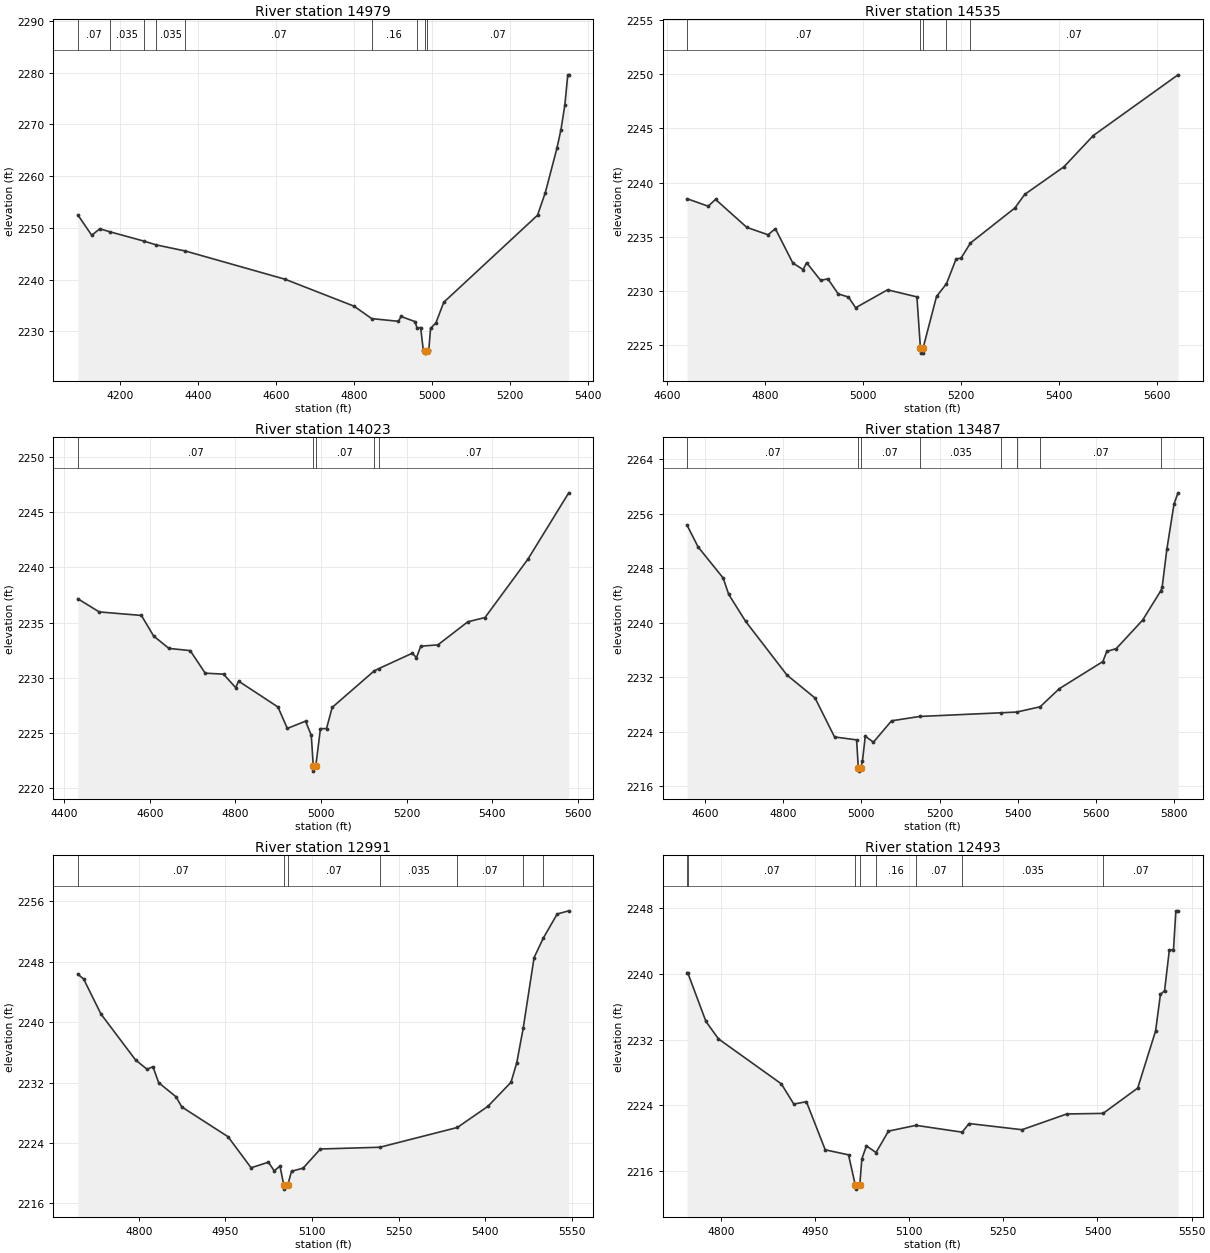
Type RM Length L Ch R = 1,14979,444,444,444
BEGIN DESCRIPTION:
Sweetwater Creek Trib 27 T2 16.0
END DESCRIPTION:
XS GIS Cut Line= 3
      1352005.02      6879887.99      1352686.73      6879288.21
      1352705.00      6878937.98
#Sta/Elev= 30
  4092.0 2252.50  4127.6 2248.56  4148.4 2249.82  4173.3 2249.25  4260.6 2247.45
  4293.5 2246.69  4367.6 2245.52  4623.8 2240.05  4800.3 2234.85  4845.5 2232.45
  4914.1 2231.93  4920.7 2232.87  4956.8 2231.86  4961.5 2230.66  4971.0 2230.72
  4977.7 2226.39  4981.6 2226.28  4982.0 2225.78  4987.2 2226.28  4991.9 2226.41
  4996.4 2230.57  5010.2 2231.64  5030.2 2235.61  5270.6 2252.43  5290.6 2256.80
  5320.6 2265.44  5330.7 2268.96  5340.7 2273.73  5348.2 2279.57  5350.7 2279.57
#Mann=9,-1,0
  4092.0    0.07       0  4173.3   0.035       0  4260.6    0.07       0
  4293.5   0.035       0  4367.6    0.07       0  4845.5    0.16       0
  4961.5    0.07       0  4981.6    0.07       0  4987.2    0.07       0
Bank Sta=4981.6,4987.2
Exp/Cntr=0.3,0.1

Type RM Length L Ch R = 1,14535,512,512,512
BEGIN DESCRIPTION:
Sweetwater Creek Trib 27 T2 15.0
END DESCRIPTION:
XS GIS Cut Line= 3
      1352805.03      6879737.96      1353024.30      6879424.10
      1353030.56      6878805.21
#Sta/Elev= 30
  4641.2 2238.51  4684.3 2237.82  4699.2 2238.45  4763.1 2235.87  4806.4 2235.19
  4821.3 2235.75  4857.0 2232.59  4878.0 2231.98  4885.1 2232.62  4913.7 2230.99
  4928.5 2231.13  4949.5 2229.75  4970.5 2229.45  4985.2 2228.47  5050.2 2230.12
  5110.2 2229.47  5117.3 2224.79  5117.8 2224.29  5122.6 2224.29  5123.0 2224.79
  5150.2 2229.51  5170.4 2230.67  5190.2 2232.97  5200.2 2233.03  5219.4 2234.43
  5310.2 2237.66  5330.2 2238.91  5410.2 2241.45  5470.2 2244.33  5643.0 2249.92
#Mann=5,-1,0
  4641.2    0.07       0  5117.3    0.07       0  5123.0    0.07       0
  5170.4    0.16       0  5219.4    0.07       0
Bank Sta=5117.3,5123
Exp/Cntr=0.3,0.1

Type RM Length L Ch R = 1,14023,536,536,536
BEGIN DESCRIPTION:
Sweetwater Creek Trib 27 T2 14.0
END DESCRIPTION:
XS GIS Cut Line= 3
      1353054.99      6879838.01      1353429.36      6879410.71
      1353444.77      6878832.52
#Sta/Elev= 30
  4431.9 2237.16  4481.7 2235.97  4580.4 2235.65  4608.9 2233.79  4644.6 2232.67
  4694.3 2232.47  4729.4 2230.43  4772.1 2230.34  4800.6 2229.12  4807.3 2229.71
  4899.3 2227.37  4921.1 2225.43  4963.7 2226.09  4977.1 2224.81  4981.7 2222.07
  4982.2 2221.57  4987.7 2222.07  4998.5 2225.41  5012.7 2225.42  5025.9 2227.33
  5124.1 2230.64  5134.6 2230.84  5212.8 2232.23  5222.8 2231.84  5232.8 2232.87
  5272.8 2232.99  5342.8 2235.08  5382.8 2235.46  5482.9 2240.73  5578.4 2246.74
#Mann=5,-1,0
  4431.9    0.07       0  4981.7    0.07       0  4987.7    0.07       0
  5124.1   0.035       0  5134.6    0.07       0
Bank Sta=4981.7,4987.7
Exp/Cntr=0.3,0.1

Type RM Length L Ch R = 1,13487,496,496,496
BEGIN DESCRIPTION:
Sweetwater Creek Trib 27 T2 13.0
END DESCRIPTION:
XS GIS Cut Line= 3
      1354055.02      6880038.03      1353777.76      6879688.30
      1353905.01      6878887.95
#Sta/Elev= 30
  4553.7 2254.34  4581.8 2251.16  4645.9 2246.60  4660.3 2244.18  4703.6 2240.22
  4809.3 2232.34  4881.4 2228.96  4931.1 2223.25  4987.6 2222.82  4992.0 2218.73
  4992.5 2218.23  4998.4 2218.73  5002.7 2219.74  5009.8 2223.36  5030.7 2222.48
  5077.1 2225.62  5149.4 2226.26  5358.4 2226.80  5398.0 2226.91  5457.4 2227.68
  5506.6 2230.34  5618.0 2234.32  5628.1 2235.81  5652.3 2236.22  5719.6 2240.39
  5766.4 2244.72  5769.8 2245.22  5781.8 2250.80  5800.2 2257.45  5810.4 2259.10
#Mann=8,-1,0
  4553.7    0.07       0  4992.0    0.07       0  4998.4    0.07       0
  5149.4   0.035       0  5358.4    0.07       0  5398.0   0.035       0
  5457.4    0.07       0  5766.4    0.16       0
Bank Sta=4992,4998.4
Exp/Cntr=0.3,0.1

Type RM Length L Ch R = 1,12991,498,498,498
BEGIN DESCRIPTION:
Sweetwater Creek Trib 27 T2 12.0
END DESCRIPTION:
XS GIS Cut Line= 3
      1354205.00      6879887.95      1354207.19      6879582.56
      1354205.00      6879037.97
#Sta/Elev= 30
  4694.6 2246.36  4704.6 2245.73  4734.6 2241.09  4794.6 2234.99  4814.6 2233.76
  4824.6 2234.11  4834.6 2231.98  4864.6 2230.12  4874.6 2228.77  4954.6 2224.83
  4994.6 2220.71  5024.6 2221.45  5034.6 2220.30  5044.6 2220.94  5051.3 2218.38
  5051.8 2217.88  5057.9 2218.38  5064.6 2220.25  5084.6 2220.66  5114.6 2223.20
  5217.6 2223.43  5351.7 2226.05  5404.6 2228.85  5444.6 2232.04  5454.6 2234.63
  5465.7 2239.19  5484.6 2248.57  5500.7 2251.17  5524.6 2254.34  5544.6 2254.76
#Mann=7,-1,0
  4694.6    0.07       0  5051.3    0.07       0  5057.9    0.07       0
  5217.6   0.035       0  5351.7    0.07       0  5465.7    0.16       0
  5500.7    0.07       0
Bank Sta=5051.3,5057.9
Exp/Cntr=0.3,0.1

Type RM Length L Ch R = 1,12493,497,497,497
BEGIN DESCRIPTION:
Sweetwater Creek Trib 27 T2 11.0
END DESCRIPTION:
XS GIS Cut Line= 3
      1354904.99      6879538.00      1354651.49      6879536.75
      1354304.97      6879137.97
#Sta/Elev= 30
  4746.5 2240.11  4747.5 2240.11  4776.5 2234.20  4796.5 2232.08  4896.5 2226.63
  4916.5 2224.17  4936.5 2224.46  4966.5 2218.62  5003.6 2218.01  5014.3 2214.35
  5014.8 2213.85  5021.5 2214.35  5024.8 2217.52  5032.1 2219.10  5047.4 2218.29
  5067.2 2220.89  5111.0 2221.59  5184.7 2220.76  5195.5 2221.81  5279.9 2221.06
  5351.2 2222.97  5409.0 2223.04  5464.1 2226.11  5492.6 2233.04  5500.3 2237.47
  5506.9 2237.93  5514.5 2242.87  5521.1 2242.91  5524.9 2247.62  5528.3 2247.62
#Mann=8,-1,0
  4746.5   0.035       0  4747.5    0.07       0  5014.3    0.07       0
  5021.5    0.07       0  5047.4    0.16       0  5111.0    0.07       0
  5184.7   0.035       0  5409.0    0.07       0
Bank Sta=5014.3,5021.5
Exp/Cntr=0.3,0.1

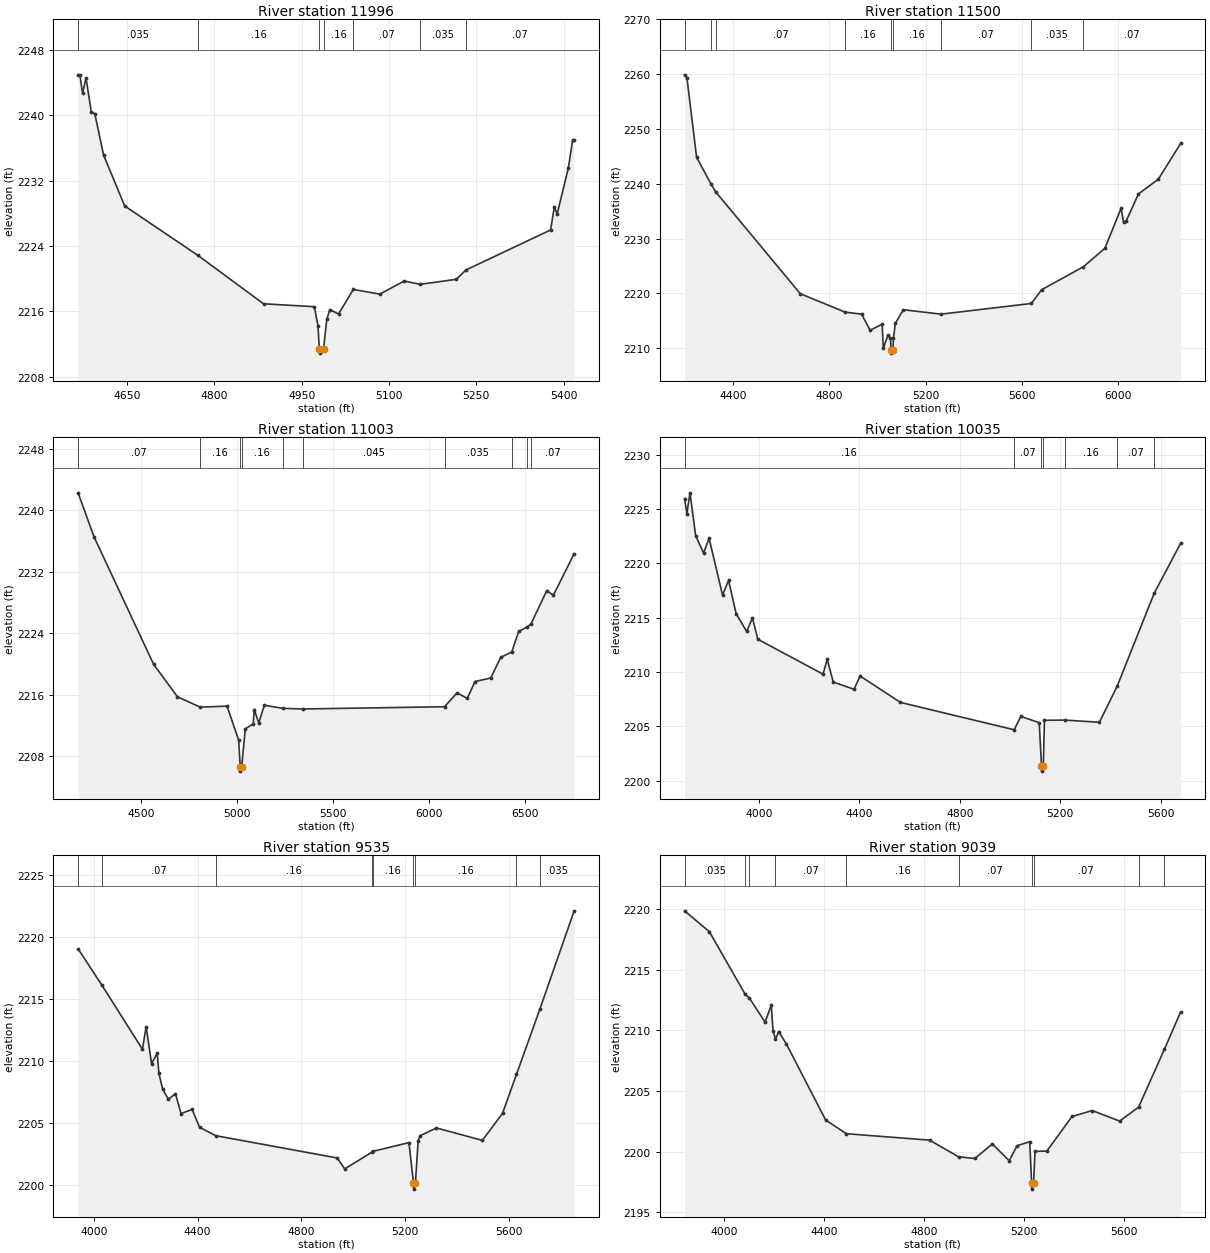
Type RM Length L Ch R = 1,11996,496,496,496
BEGIN DESCRIPTION:
Sweetwater Creek Trib 27 T2 10.0
END DESCRIPTION:
XS GIS Cut Line= 3
      1355005.02      6879438.04      1354768.23      6879074.33
      1354355.00      6879138.00
#Sta/Elev= 30
  4566.0 2244.95  4569.0 2244.95  4573.6 2242.72  4579.6 2244.56  4588.7 2240.40
  4594.7 2240.19  4609.8 2235.12  4646.1 2228.90  4771.4 2222.88  4884.5 2216.94
  4971.8 2216.58  4978.1 2214.24  4980.4 2211.40  4980.9 2210.90  4987.6 2211.40
  4993.2 2215.04  4998.4 2216.22  5013.4 2215.69  5038.7 2218.69  5084.2 2218.12
  5126.2 2219.72  5153.6 2219.32  5215.7 2219.93  5232.2 2221.07  5377.6 2225.97
  5384.0 2228.75  5389.0 2227.94  5408.0 2233.51  5415.6 2236.98  5418.1 2236.98
#Mann=7,-1,0
  4566.0   0.035       0  4771.4    0.16       0  4980.4    0.07       0
  4987.6    0.16       0  5038.7    0.07       0  5153.6   0.035       0
  5232.2    0.07       0
Bank Sta=4980.4,4987.6
Exp/Cntr=0.3,0.1

Type RM Length L Ch R = 1,11500,497,497,497
BEGIN DESCRIPTION:
Sweetwater Creek Trib 27 T2 9.0
END DESCRIPTION:
XS GIS Cut Line= 3
      1355155.00      6879588.00      1355127.75      6878788.06
      1353905.03      6878488.01
#Sta/Elev= 30
  4199.6 2259.90  4209.6 2259.32  4249.6 2244.84  4308.7 2240.04  4329.0 2238.54
  4679.9 2219.97  4865.6 2216.61  4934.5 2216.23  4970.0 2213.30  5019.8 2214.39
  5024.9 2209.99  5044.0 2212.42  5054.3 2211.86  5057.7 2209.62  5058.2 2209.12
  5064.9 2209.62  5066.5 2211.80  5074.9 2214.56  5108.1 2217.04  5264.3 2216.23
  5639.2 2218.18  5682.4 2220.70  5854.6 2224.85  5944.7 2228.25  6011.9 2235.55
  6022.2 2232.97  6033.0 2233.22  6084.0 2238.17  6166.4 2240.85  6259.0 2247.37
#Mann=9,-1,0
  4199.6    0.07       0  4308.7   0.035       0  4329.0    0.07       0
  4865.6    0.16       0  5057.7    0.07       0  5064.9    0.16       0
  5264.3    0.07       0  5639.2   0.035       0  5854.6    0.07       0
Bank Sta=5057.7,5064.9
Exp/Cntr=0.3,0.1

Type RM Length L Ch R = 1,11003,968,968,968
BEGIN DESCRIPTION:
Sweetwater Creek Trib 27 T2 8.0
END DESCRIPTION:
XS GIS Cut Line= 3
      1355355.00      6879488.01      1355564.28      6878688.45
      1353955.01      6877988.00
#Sta/Elev= 30
  4173.5 2242.24  4256.2 2236.53  4566.3 2219.96  4690.4 2215.73  4808.9 2214.38
  4948.8 2214.51  5009.2 2210.07  5017.4 2206.56  5017.9 2206.06  5024.7 2206.56
  5043.5 2211.55  5084.9 2212.21  5090.4 2214.07  5113.8 2212.31  5142.7 2214.63
  5238.9 2214.22  5345.1 2214.14  6080.4 2214.43  6145.5 2216.23  6198.9 2215.52
  6239.3 2217.71  6320.5 2218.16  6373.4 2220.86  6430.4 2221.55  6466.5 2224.22
  6512.3 2224.83  6531.4 2225.23  6612.6 2229.53  6646.9 2228.92  6755.1 2234.33
#Mann=10,-1,0
  4173.5    0.07       0  4808.9    0.16       0  5017.4    0.07       0
  5024.7    0.16       0  5238.9    0.07       0  5345.1   0.045       0
  6080.4   0.035       0  6430.4    0.07       0  6512.3   0.035       0
  6531.4    0.07       0
Bank Sta=5017.4,5024.7
Exp/Cntr=0.3,0.1

Type RM Length L Ch R = 1,10035,500,500,500
BEGIN DESCRIPTION:
Sweetwater Creek Trib 27 T2 7.0
END DESCRIPTION:
XS GIS Cut Line= 3
      1355755.01      6879337.98      1356245.29      6878139.27
      1356055.00      6877488.00
#Sta/Elev= 30
  3704.9 2225.96  3714.2 2224.59  3726.5 2226.50  3749.0 2222.56  3780.5 2220.95
  3802.4 2222.31  3856.1 2217.08  3879.9 2218.44  3910.2 2215.37  3951.9 2213.73
  3975.0 2214.97  3996.6 2213.01  4255.9 2209.80  4272.5 2211.18  4296.5 2209.07
  4379.3 2208.41  4403.3 2209.63  4563.6 2207.20  5016.2 2204.68  5043.0 2205.91
  5115.9 2205.33  5125.0 2201.37  5125.5 2200.87  5132.3 2201.37  5136.8 2205.55
  5216.9 2205.57  5355.5 2205.37  5426.4 2208.71  5573.4 2217.25  5678.5 2221.85
#Mann=7,-1,0
  3704.9    0.16       0  5016.2    0.07       0  5125.0    0.07       0
  5132.3    0.07       0  5216.9    0.16       0  5426.4    0.07       0
  5573.4   0.035       0
Bank Sta=5125,5132.3
Exp/Cntr=0.3,0.1

Type RM Length L Ch R = 1,9535,496,496,496
BEGIN DESCRIPTION:
Sweetwater Creek Trib 27 T2 6.0
END DESCRIPTION:
XS GIS Cut Line= 3
      1357404.99      6878887.99      1356699.07      6878096.44
      1356104.98      6877487.98
#Sta/Elev= 30
  3939.4 2219.03  4030.7 2216.11  4187.3 2210.93  4201.5 2212.76  4222.4 2209.78
  4244.1 2210.61  4250.8 2208.98  4265.0 2207.74  4286.8 2206.91  4314.6 2207.34
  4336.1 2205.75  4378.7 2206.08  4407.2 2204.65  4468.9 2203.97  4938.1 2202.17
  4966.5 2201.29  5072.4 2202.65  5076.4 2202.71  5213.9 2203.41  5231.5 2200.16
  5232.0 2199.66  5238.9 2200.16  5249.4 2203.55  5256.4 2203.96  5319.9 2204.59
  5496.8 2203.59  5574.5 2205.77  5628.3 2208.91  5718.9 2214.20  5850.4 2222.09
#Mann=9,-1,0
  3939.4   0.035       0  4030.7    0.07       0  4468.9    0.16       0
  5072.4    0.07       0  5076.4    0.16       0  5231.5    0.07       0
  5238.9    0.16       0  5628.3    0.07       0  5718.9   0.035       0
Bank Sta=5231.5,5238.9
Exp/Cntr=0.3,0.1

Type RM Length L Ch R = 1,9039,435,435,435
BEGIN DESCRIPTION:
Sweetwater Creek Trib 27 T2 5.0
END DESCRIPTION:
XS GIS Cut Line= 3
      1357504.98      6878887.95      1357085.02      6877808.04
      1356304.53      6877537.94
#Sta/Elev= 30
  3841.3 2219.86  3940.5 2218.14  4083.8 2212.98  4099.6 2212.70  4163.5 2210.68
  4188.0 2212.08  4195.3 2209.98  4205.1 2209.27  4217.9 2209.90  4249.0 2208.87
  4405.7 2202.61  4488.9 2201.48  4821.9 2200.95  4937.8 2199.57  5002.7 2199.44
  5072.7 2200.63  5140.3 2199.25  5171.5 2200.49  5222.2 2200.82  5229.9 2197.41
  5230.4 2196.91  5237.6 2197.41  5243.4 2200.02  5290.8 2200.05  5391.5 2202.90
  5472.5 2203.39  5582.0 2202.52  5657.7 2203.67  5761.4 2208.46  5825.9 2211.52
#Mann=10,-1,0
  3841.3   0.035       0  4083.8    0.07       0  4099.6   0.035       0
  4205.1    0.07       0  4488.9    0.16       0  4937.8    0.07       0
  5229.9    0.07       0  5237.6    0.07       0  5657.7    0.16       0
  5761.4   0.035       0
Bank Sta=5229.9,5237.6
Exp/Cntr=0.3,0.1

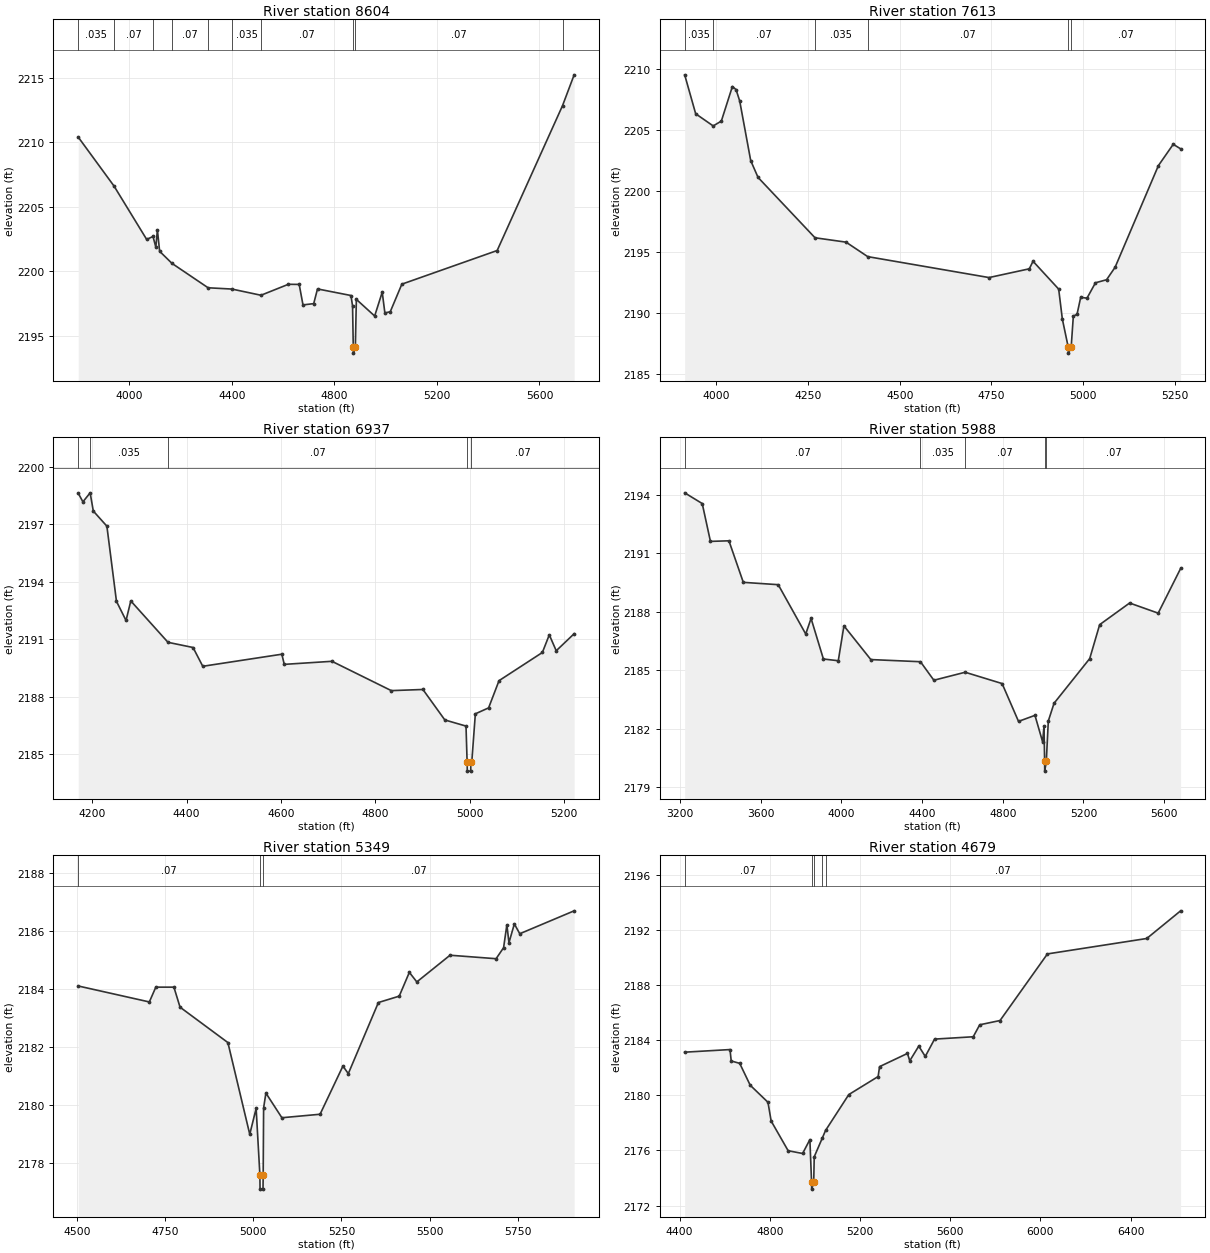
Type RM Length L Ch R = 1,8604,991,991,991
BEGIN DESCRIPTION:
Sweetwater Creek Trib 27 T2 4.0
END DESCRIPTION:
XS GIS Cut Line= 3
      1357856.50      6878457.58      1357165.17      6877478.32
      1356455.03      6877288.01
#Sta/Elev= 30
  3801.3 2210.41  3941.0 2206.61  4068.3 2202.47  4092.9 2202.70  4104.0 2201.87
  4110.1 2203.21  4118.8 2201.55  4167.1 2200.61  4307.8 2198.72  4400.7 2198.62
  4514.0 2198.14  4620.9 2198.99  4663.0 2198.98  4677.8 2197.39  4719.6 2197.49
  4734.4 2198.63  4864.9 2198.12  4871.1 2197.31  4873.9 2194.15  4874.4 2193.65
  4882.0 2194.15  4885.9 2197.82  4957.3 2196.53  4986.8 2198.38  4997.1 2196.77
  5018.1 2196.86  5063.3 2199.00  5435.0 2201.61  5689.9 2212.85  5735.2 2215.24
#Mann=10,-1,0
  3801.3   0.035       0  3941.0    0.07       0  4092.9    0.16       0
  4167.1    0.07       0  4307.8    0.16       0  4400.7   0.035       0
  4514.0    0.07       0  4873.9    0.07       0  4882.0    0.07       0
  5689.9   0.035       0
Bank Sta=4873.9,4882
Exp/Cntr=0.3,0.1

Type RM Length L Ch R = 1,7613,676,676,676
BEGIN DESCRIPTION:
Sweetwater Creek Trib 27 T2 3.0
END DESCRIPTION:
XS GIS Cut Line= 3
      1357955.00      6878288.04      1357968.20      6877201.62
      1358005.00      6876937.98
#Sta/Elev= 30
  3913.5 2209.55  3943.5 2206.35  3991.3 2205.35  4013.5 2205.75  4043.6 2208.59
  4053.6 2208.34  4063.6 2207.40  4093.6 2202.50  4113.6 2201.12  4269.0 2196.16
  4353.6 2195.80  4412.8 2194.61  4743.6 2192.89  4853.6 2193.61  4863.6 2194.23
  4933.6 2191.94  4943.6 2189.48  4959.6 2187.18  4960.1 2186.68  4967.7 2187.18
  4973.6 2189.73  4983.6 2189.86  4993.6 2191.26  5010.9 2191.20  5033.9 2192.46
  5064.2 2192.71  5087.4 2193.73  5205.6 2202.09  5246.0 2203.84  5266.2 2203.47
#Mann=6,-1,0
  3913.5   0.035       0  3991.3    0.07       0  4269.0   0.035       0
  4412.8    0.07       0  4959.6    0.07       0  4967.7    0.07       0
Bank Sta=4959.6,4967.7
Exp/Cntr=0.3,0.1

Type RM Length L Ch R = 1,6937,949,949,949
BEGIN DESCRIPTION:
Sweetwater Creek Trib 27 T2 4121
END DESCRIPTION:
XS GIS Cut Line= 3
      1358455.02      6878057.83      1358598.97      6877240.51
      1358468.04      6877061.60
#Sta/Elev= 30
  4170.1 2198.61  4180.1 2198.16  4195.4 2198.63  4202.1 2197.68  4230.9 2196.89
  4251.2 2192.97  4271.5 2191.97  4281.6 2192.99  4360.5 2190.83  4413.6 2190.56
  4434.2 2189.58  4601.9 2190.21  4607.0 2189.68  4708.1 2189.84  4834.0 2188.31
  4901.0 2188.37  4947.5 2186.78  4992.4 2186.46  4994.7 2184.61  4995.2 2184.11
  5002.3 2184.11  5002.8 2184.61  5004.7 2184.61  5012.2 2187.10  5040.3 2187.41
  5062.4 2188.83  5154.3 2190.30  5169.0 2191.22  5183.7 2190.39  5221.7 2191.28
#Mann=5,-1,0
  4170.1    0.07       0  4195.4   0.035       0  4360.5    0.07       0
  4994.7    0.07       0  5002.8    0.07       0
Bank Sta=4994.7,5002.8
Exp/Cntr=0.3,0.1

Type RM Length L Ch R = 1,5988,639,639,639
BEGIN DESCRIPTION:
Sweetwater Creek Trib 27 T2 4122
END DESCRIPTION:
XS GIS Cut Line= 3
      1358857.54      6879333.41      1359191.09      6877588.40
      1358723.47      6877092.36
#Sta/Elev= 30
  3223.4 2194.09  3310.4 2193.54  3351.1 2191.60  3442.7 2191.63  3514.0 2189.50
  3687.1 2189.38  3823.5 2186.85  3849.9 2187.65  3911.0 2185.57  3984.8 2185.48
  4012.8 2187.27  4146.1 2185.54  4392.1 2185.43  4458.6 2184.48  4613.7 2184.89
  4796.8 2184.31  4878.2 2182.37  4959.7 2182.68  4997.7 2181.32  5004.5 2182.13
  5007.6 2180.32  5008.1 2179.82  5015.9 2180.32  5025.9 2182.39  5054.3 2183.30
  5231.1 2185.59  5280.4 2187.33  5428.9 2188.44  5570.5 2187.92  5681.7 2190.21
#Mann=5,-1,0
  3223.4    0.07       0  4392.1   0.035       0  4613.7    0.07       0
  5007.6    0.07       0  5015.9    0.07       0
Bank Sta=5007.6,5015.9
Exp/Cntr=0.3,0.1

Type RM Length L Ch R = 1,5349,670,670,670
BEGIN DESCRIPTION:
Sweetwater Creek Trib 27 T2 2.0
END DESCRIPTION:
XS GIS Cut Line= 3
      1359813.13      6878122.90      1359705.38      6877638.33
      1358935.15      6877153.52
#Sta/Elev= 30
  4503.6 2184.11  4705.3 2183.56  4723.7 2184.07  4775.0 2184.07  4792.4 2183.38
  4928.1 2182.16  4990.1 2179.00  5008.2 2179.89  5018.8 2177.61  5019.3 2177.11
  5027.7 2177.11  5028.2 2177.61  5029.4 2179.91  5035.9 2180.42  5081.2 2179.57
  5189.5 2179.69  5254.3 2181.35  5269.6 2181.09  5354.9 2183.54  5414.0 2183.76
  5442.7 2184.58  5463.9 2184.25  5558.1 2185.17  5688.7 2185.05  5710.0 2185.43
  5719.3 2186.22  5725.2 2185.60  5740.5 2186.25  5755.8 2185.91  5910.1 2186.70
#Mann=3,-1,0
  4503.6    0.07       0  5018.8    0.07       0  5028.2    0.07       0
Bank Sta=5018.8,5028.2
Exp/Cntr=0.3,0.1

Type RM Length L Ch R = 1,4679,277,277,277
BEGIN DESCRIPTION:
Sweetwater Creek Trib 27 T2 1.0
END DESCRIPTION:
XS GIS Cut Line= 3
      1360085.09      6877605.24      1359874.90      6877067.03
      1358255.03      6876988.00
#Sta/Elev= 30
  4422.2 2183.14  4623.2 2183.33  4628.6 2182.50  4666.2 2182.33  4712.8 2180.74
  4791.6 2179.50  4805.7 2178.14  4881.1 2175.98  4945.3 2175.78  4977.5 2176.79
  4985.0 2173.69  4985.5 2173.19  4994.5 2173.69  4996.8 2175.54  5033.1 2176.92
  5046.9 2177.45  5150.1 2180.06  5280.2 2181.37  5286.6 2182.09  5410.4 2183.05
  5420.4 2182.51  5460.4 2183.58  5489.3 2182.83  5530.5 2184.09  5702.0 2184.26
  5730.8 2185.13  5820.9 2185.44  6031.1 2190.28  6471.6 2191.40  6621.8 2193.41
#Mann=5,-1,0
  4422.2    0.07       0  4985.0    0.07       0  4994.5    0.07       0
  5033.1    0.16       0  5046.9    0.07       0
Bank Sta=4985,4994.5
Exp/Cntr=0.3,0.1

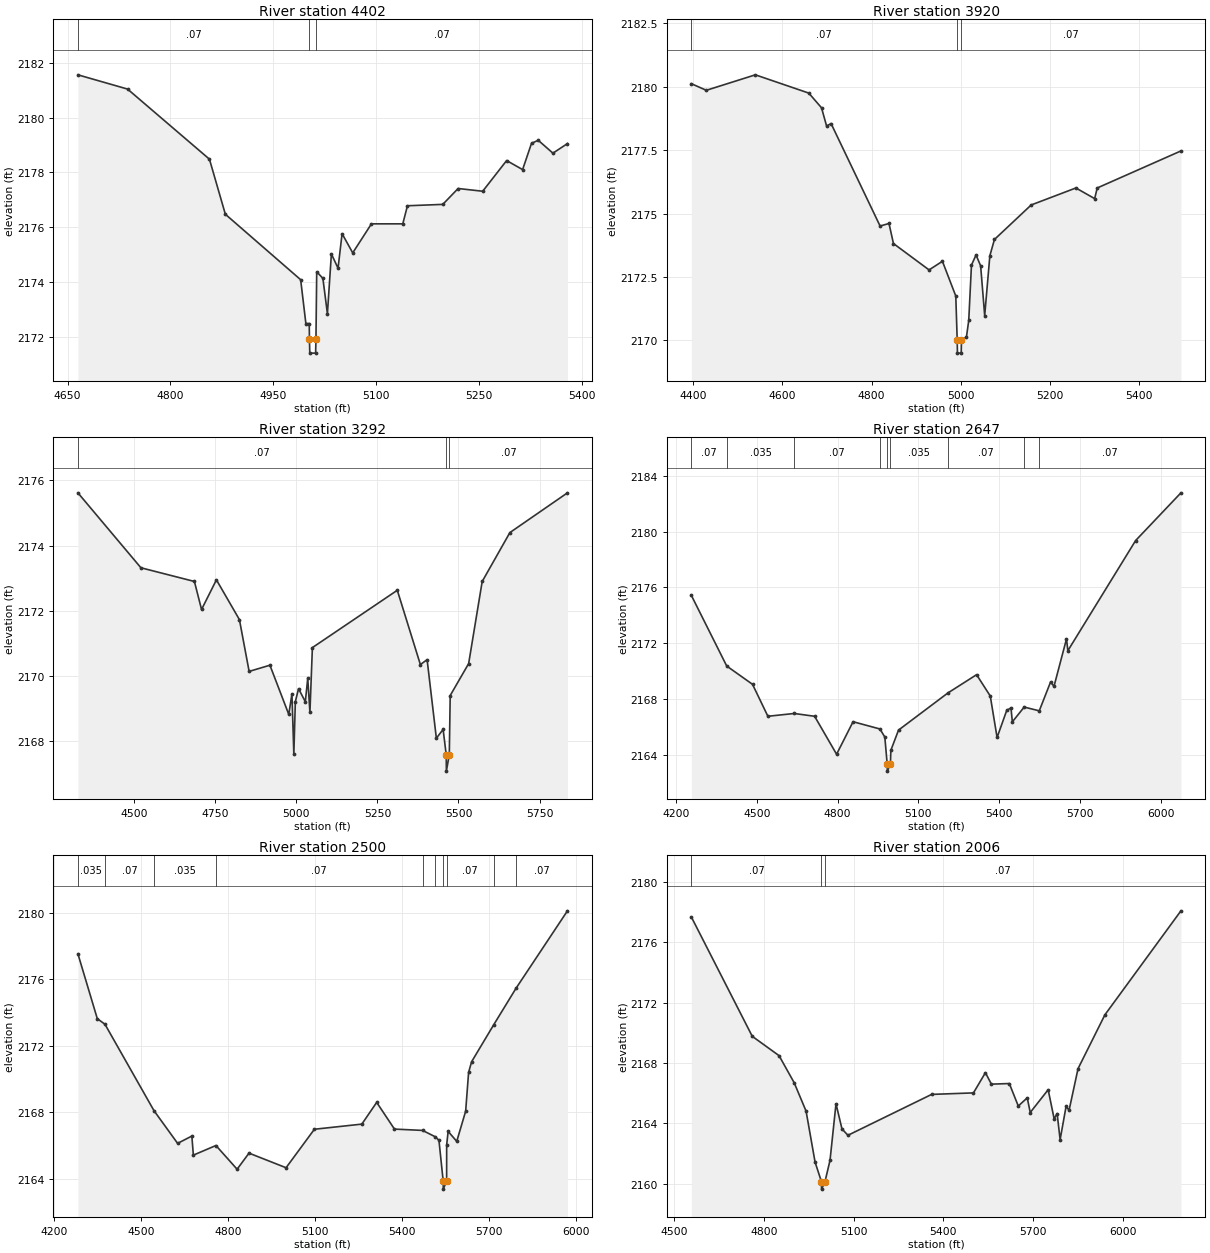
Type RM Length L Ch R = 1,4402,482,482,482
BEGIN DESCRIPTION:
Sweetwater Creek Trib 27 T2 4116
END DESCRIPTION:
XS GIS Cut Line= 3
      1360184.89      6877365.51      1360114.16      6877038.17
      1359788.90      6876843.83
#Sta/Elev= 30
  4665.1 2181.56  4737.5 2181.04  4856.9 2178.48  4880.1 2176.47  4989.9 2174.08
  4997.5 2172.48  5002.4 2172.48  5002.7 2171.90  5003.2 2171.40  5011.7 2171.40
  5012.2 2171.90  5013.3 2174.37  5022.3 2174.13  5028.9 2172.84  5034.7 2175.02
  5044.4 2174.50  5050.3 2175.76  5065.8 2175.06  5093.1 2176.12  5138.8 2176.12
  5145.6 2176.78  5197.1 2176.83  5219.5 2177.41  5255.3 2177.31  5290.2 2178.43
  5313.5 2178.10  5326.5 2179.06  5336.3 2179.17  5357.7 2178.70  5378.9 2179.05
#Mann=3,-1,0
  4665.1    0.07       0  5002.7    0.07       0  5012.2    0.07       0
Bank Sta=5002.7,5012.2
Exp/Cntr=0.3,0.1

Type RM Length L Ch R = 1,3920,628,628,628
BEGIN DESCRIPTION:
Sweetwater Creek Trib 27 T2 4115
END DESCRIPTION:
XS GIS Cut Line= 4
      1360351.70      6877341.61      1360368.66      6876737.25
      1360088.13      6876666.07      1359909.82      6876768.00
#Sta/Elev= 30
  4395.4 2180.12  4429.0 2179.86  4539.1 2180.47  4659.1 2179.75  4687.7 2179.17
  4699.1 2178.45  4709.1 2178.55  4819.2 2174.51  4839.2 2174.61  4849.2 2173.82
  4929.2 2172.78  4959.2 2173.12  4989.2 2171.75  4992.4 2170.00  4992.9 2169.50
  5001.4 2169.50  5001.9 2170.00  5013.1 2170.13  5018.3 2170.79  5024.4 2172.97
  5034.7 2173.37  5045.0 2172.94  5054.1 2170.98  5065.7 2173.34  5076.0 2173.98
  5158.5 2175.34  5258.9 2176.01  5301.1 2175.59  5306.8 2176.01  5494.8 2177.47
#Mann=3,-1,0
  4395.4    0.07       0  4992.4    0.07       0  5001.9    0.07       0
Bank Sta=4992.4,5001.9
Exp/Cntr=0.3,0.1

Type RM Length L Ch R = 1,3292,645,645,645
BEGIN DESCRIPTION:
Sweetwater Creek Trib 27 T2 4392
END DESCRIPTION:
XS GIS Cut Line= 3
      1360546.61      6877414.51      1360894.81      6876837.54
      1360343.50      6876208.82
#Sta/Elev= 30
  4326.1 2175.62  4520.5 2173.32  4685.5 2172.90  4707.5 2172.04  4753.4 2172.95
  4824.3 2171.73  4854.3 2170.14  4918.4 2170.33  4976.6 2168.82  4986.3 2169.45
  4992.2 2167.60  4996.8 2169.21  5006.7 2169.61  5027.6 2169.21  5035.1 2169.93
  5041.8 2168.88  5049.4 2170.87  5311.3 2172.63  5382.5 2170.35  5403.3 2170.50
  5431.8 2168.09  5452.7 2168.36  5462.2 2167.58  5462.7 2167.08  5471.7 2167.58
  5474.5 2169.40  5531.4 2170.38  5573.2 2172.90  5658.6 2174.40  5836.2 2175.62
#Mann=3,-1,0
  4326.1    0.07       0  5462.2    0.07       0  5471.7    0.07       0
Bank Sta=5462.2,5471.7
Exp/Cntr=0.3,0.1

Type RM Length L Ch R = 1,2647,147,147,147
BEGIN DESCRIPTION:
Sweetwater Creek Trib 27 T2 4391
END DESCRIPTION:
XS GIS Cut Line= 3
      1361234.09      6877896.35      1361384.92      6877168.21
      1361590.83      6876112.70
#Sta/Elev= 30
  4256.4 2175.43  4387.8 2170.37  4483.6 2169.06  4540.7 2166.77  4638.5 2166.97
  4714.3 2166.77  4796.0 2164.05  4857.2 2166.38  4957.0 2165.86  4975.2 2165.28
  4984.0 2163.34  4984.5 2162.84  4996.0 2163.34  4997.6 2164.33  5026.1 2165.78
  5209.5 2168.44  5316.1 2169.75  5367.0 2168.22  5392.3 2165.25  5428.1 2167.19
  5443.9 2167.37  5449.0 2166.37  5493.0 2167.43  5549.0 2167.16  5591.1 2169.23
  5603.7 2168.91  5650.2 2172.31  5655.3 2171.47  5907.0 2179.36  6075.4 2182.78
#Mann=9,-1,0
  4256.4    0.07       0  4387.8   0.035       0  4638.5    0.07       0
  4957.0   0.035       0  4984.0   0.035       0  4996.0   0.035       0
  5209.5    0.07       0  5493.0   0.035       0  5549.0    0.07       0
Bank Sta=4984,4996
Exp/Cntr=0.3,0.1

Type RM Length L Ch R = 1,2500,494,494,494
BEGIN DESCRIPTION:
Sweetwater Creek Trib 27 T2 4390
END DESCRIPTION:
XS GIS Cut Line= 3
      1361340.88      6877943.15      1361502.43      6877243.46
      1361708.05      6876294.79
#Sta/Elev= 30
  4281.9 2177.55  4348.8 2173.64  4375.3 2173.30  4544.4 2168.09  4625.9 2166.12
  4675.0 2166.56  4680.2 2165.41  4758.1 2165.99  4831.1 2164.56  4872.2 2165.53
  5000.0 2164.65  5097.7 2166.97  5261.4 2167.28  5312.6 2168.59  5373.9 2166.98
  5470.9 2166.90  5515.4 2166.51  5527.4 2166.30  5541.9 2163.86  5542.4 2163.36
  5553.9 2163.86  5554.0 2166.03  5559.1 2166.84  5588.8 2166.24  5619.5 2168.06
  5629.7 2170.40  5640.0 2171.04  5715.6 2173.25  5792.9 2175.46  5970.7 2180.14
#Mann=10,-1,0
  4281.9   0.035       0  4375.3    0.07       0  4544.4   0.035       0
  4758.1    0.07       0  5470.9   0.035       0  5515.4    0.07       0
  5541.9    0.07       0  5553.9    0.07       0  5715.6   0.063       0
  5792.9    0.07       0
Bank Sta=5541.9,5553.9
Exp/Cntr=0.3,0.1

Type RM Length L Ch R = 1,2006,600,600,600
BEGIN DESCRIPTION:
Sweetwater Creek Trib 27 T2 4389
END DESCRIPTION:
XS GIS Cut Line= 3
      1361820.04      6878031.73      1361834.86      6877588.48
      1361838.27      6876393.68
#Sta/Elev= 30
  4556.5 2177.68  4760.3 2169.77  4849.9 2168.49  4900.4 2166.70  4940.4 2164.81
  4970.5 2161.43  4991.7 2160.14  4992.2 2159.64  5003.7 2160.14  5020.5 2161.55
  5040.5 2165.30  5060.5 2163.63  5080.5 2163.21  5360.5 2165.92  5500.5 2166.02
  5540.5 2167.36  5560.5 2166.60  5620.5 2166.64  5650.5 2165.15  5680.5 2165.69
  5690.5 2164.72  5750.5 2166.23  5770.5 2164.30  5780.5 2164.65  5790.5 2162.92
  5810.5 2165.13  5820.5 2164.87  5850.5 2167.63  5940.5 2171.20  6194.8 2178.09
#Mann=3,-1,0
  4556.5    0.07       0  4991.7    0.07       0  5003.7    0.07       0
Bank Sta=4991.7,5003.7
Exp/Cntr=0.3,0.1