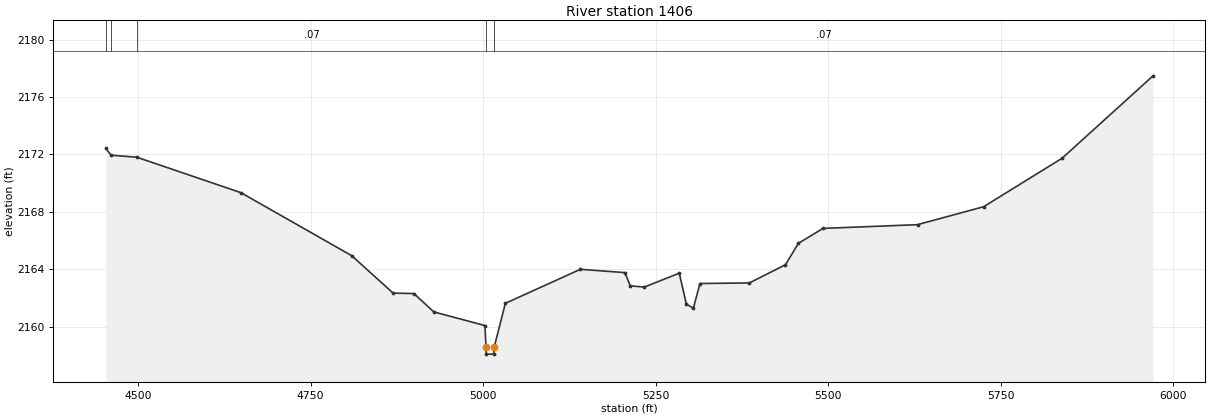
HEC-RAS study Sweetwater Creek Trib 27 T2.prj: Sweetwater Creek Trib 27 T2 Base Level Engineering

--- Sweetwater Creek Trib 27 T2.g01 (geometry) --- (continued)

Type RM Length L Ch R = 1,1406,0,0,0
BEGIN DESCRIPTION:
Sweetwater Creek Trib 27 T2 4388
END DESCRIPTION:
XS GIS Cut Line= 3
      1362335.67      6877883.27      1362294.95      6877337.89
      1362127.54      6876381.84
#Sta/Elev= 30
  4453.1 2172.43  4460.7 2171.95  4498.0 2171.81  4648.9 2169.34  4809.4 2164.95
  4869.5 2162.34  4899.6 2162.31  4928.5 2161.03  5002.5 2160.08  5004.0 2158.59
  5004.5 2158.09  5015.5 2158.09  5016.0 2158.59  5032.1 2161.63  5140.8 2164.00
  5205.3 2163.77  5213.1 2162.85  5233.4 2162.76  5284.1 2163.73  5294.3 2161.58
  5304.5 2161.29  5314.1 2163.01  5385.7 2163.05  5438.0 2164.32  5456.7 2165.81
  5492.4 2166.85  5629.3 2167.11  5725.1 2168.36  5838.9 2171.74  5970.6 2177.48
#Mann=5,-1,0
  4453.1    0.07       0  4460.7   0.035       0  4498.0    0.07       0
  5004.0    0.07       0  5016.0    0.07       0
Bank Sta=5004,5016
Exp/Cntr=0.3,0.1

Chan Stop Cuts=-1