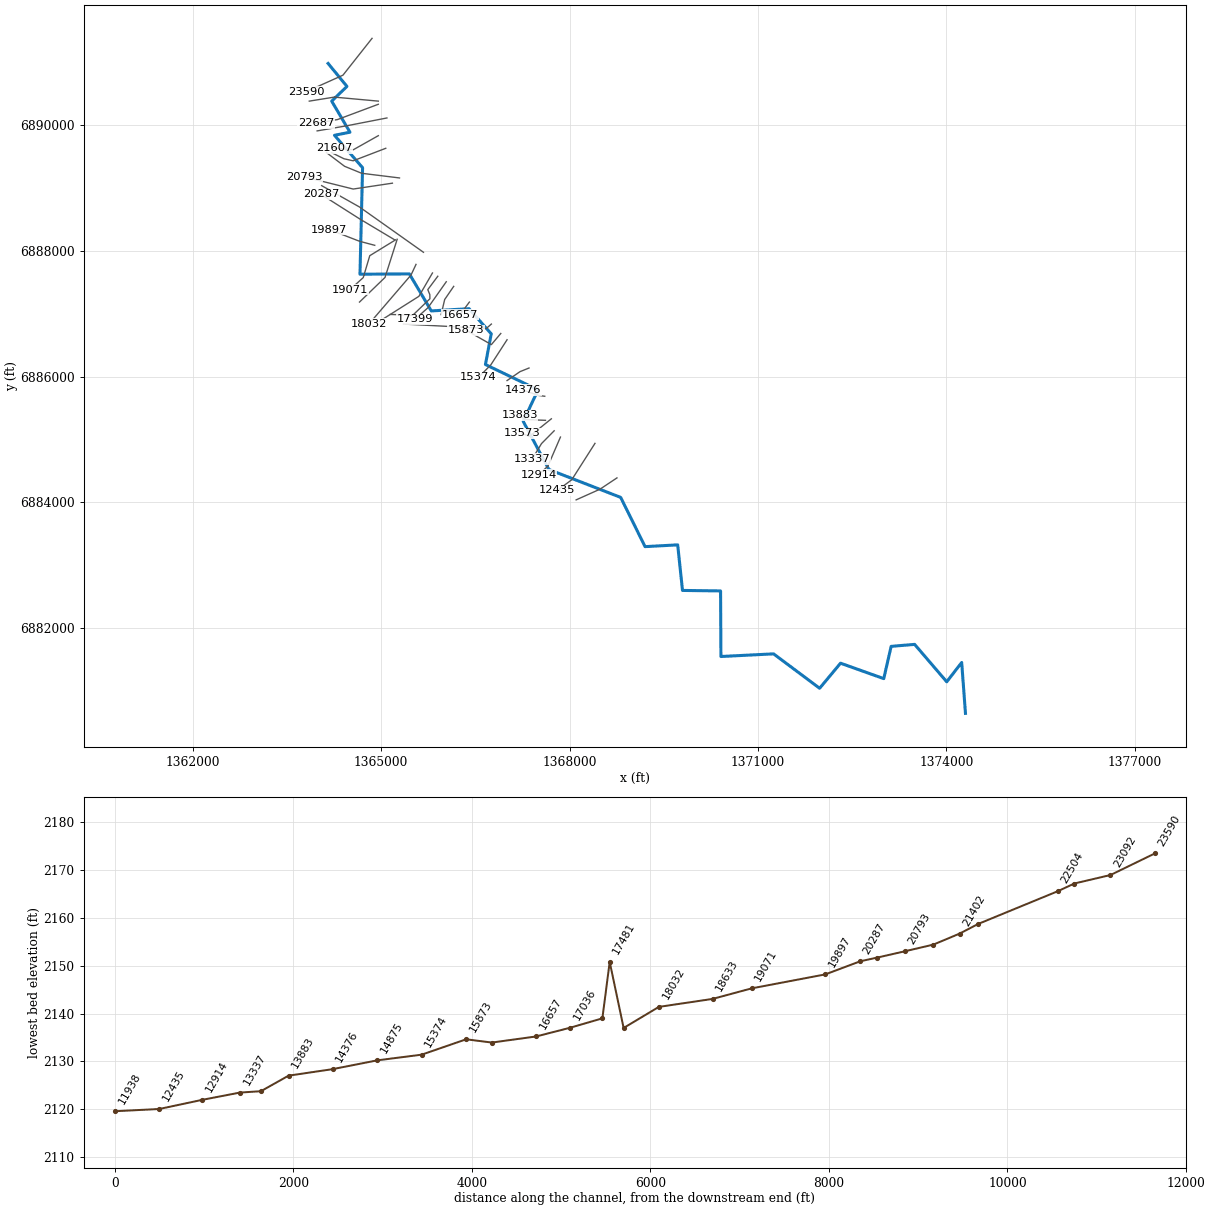
--- Sweetwater Creek Trib 27 T3.prj (project) ---

Proj Title=Sweetwater Creek Trib 27 T3 Base Level Engineering
Current Plan=p01
Default Exp/Contr=0.3,0.1
English Units
Geom File=g01
Flow File=f01
Plan File=p01
BEGIN DESCRIPTION:
Sweetwater Creek Trib 27 T3
END DESCRIPTION:

--- Sweetwater Creek Trib 27 T3.p01 (plan) ---

Plan Title=Multiple Run
Short Identifier=Multiple
Geom File=g01
Flow File=f01
Subcritical Flow
K Sum by GR= 0
Std Step Tol= 0.01
Critical Tol= 0.01
Num of Std Step Trials= 20
Max Error Tol= 0.3
Flow Tol Ratio= 0.001
Split Flow NTrial= 30
Split Flow Tol= 0.02
Split Flow Ratio= 0.02
Log Output Level= 0
Friction Slope Method= 1
Unsteady Friction Slope Method= 2
Unsteady Bridges Friction Slope Method= 1
Parabolic Critical Depth
Global Vel Dist=  1 , 1 , 1
Global Log Level= 0
CheckData=True
Encroach Param= -1, 0, 0, 0
BEGIN DESCRIPTION:
Multiple Run
END DESCRIPTION:

--- Sweetwater Creek Trib 27 T3.f01 (steady flow) ---

Flow Title=Multiple
Number of Profiles=7
Profile Names=10-year,25-year,50-year,1pct_min,100-year,1pct_plu,500-year
River Rch & RM= Sweetwater Creek,Reach-1,23590
     355     512     647     407     811    1619    1292
River Rch & RM= Sweetwater Creek,Reach-1,23092
     454     659     835     526    1049    2092    1676
River Rch & RM= Sweetwater Creek,Reach-1,18032
     488     708     897     563    1124    2243    1791
River Rch & RM= Sweetwater Creek,Reach-1,13337
     836    1247    1609    1029    2053    4096    3390
River Rch & RM= Sweetwater Creek,Reach-1,8269
     892    1326    1707    1087    2169    4328    3556
River Rch & RM= Sweetwater Creek,Reach-1,2718
     952    1416    1822    1161    2317    4623    3799
River Rch & RM= Sweetwater Creek,Reach-1,578
     947    1407    1811    1153    2301    4592    3769
Boundary for River Rch & Prof#=Sweetwater Creek,Reach-1,1
Up Type=0
Dn Type=3
Dn Slope=0.005
Boundary for River Rch & Prof#=Sweetwater Creek,Reach-1,2
Up Type=0
Dn Type=3
Dn Slope=0.005
Boundary for River Rch & Prof#=Sweetwater Creek,Reach-1,3
Up Type=0
Dn Type=3
Dn Slope=0.005
Boundary for River Rch & Prof#=Sweetwater Creek,Reach-1,4
Up Type=0
Dn Type=3
Dn Slope=0.005
Boundary for River Rch & Prof#=Sweetwater Creek,Reach-1,5
Up Type=0
Dn Type=3
Dn Slope=0.005
Boundary for River Rch & Prof#=Sweetwater Creek,Reach-1,6
Up Type=0
Dn Type=3
Dn Slope=0.005
Boundary for River Rch & Prof#=Sweetwater Creek,Reach-1,7
Up Type=0
Dn Type=3
Dn Slope=0.005

--- Sweetwater Creek Trib 27 T3.g01 (geometry) ---

Geom Title=Existing Conditions

River Reach=Sweetwater Creek,Reach-1
Reach XY= 30
      1364155.00      6890988.00      1364455.17      6890622.11
      1364212.53      6890388.01      1364503.31      6889893.22
      1364256.56      6889844.09      1364704.18      6889327.56
      1364662.74      6887631.87      1365449.57      6887636.39
      1365798.33      6887046.95      1366399.53      6887082.74
      1366752.94      6886682.15      1366660.44      6886193.25
      1367499.54      6885790.45      1367262.23      6885288.31
      1367671.41      6884521.20      1368814.71      6884077.25
      1369202.33      6883293.29      1369722.13      6883321.54
      1369798.81      6882595.81      1370405.00      6882588.00
      1370410.61      6881543.59      1371249.06      6881585.87
      1371982.45      6881037.76      1372315.48      6881437.08
      1373003.78      6881191.44      1373121.26      6881705.22
      1373495.41      6881736.79      1374006.47      6881140.99
      1374244.65      6881448.24      1374305.00      6880638.00

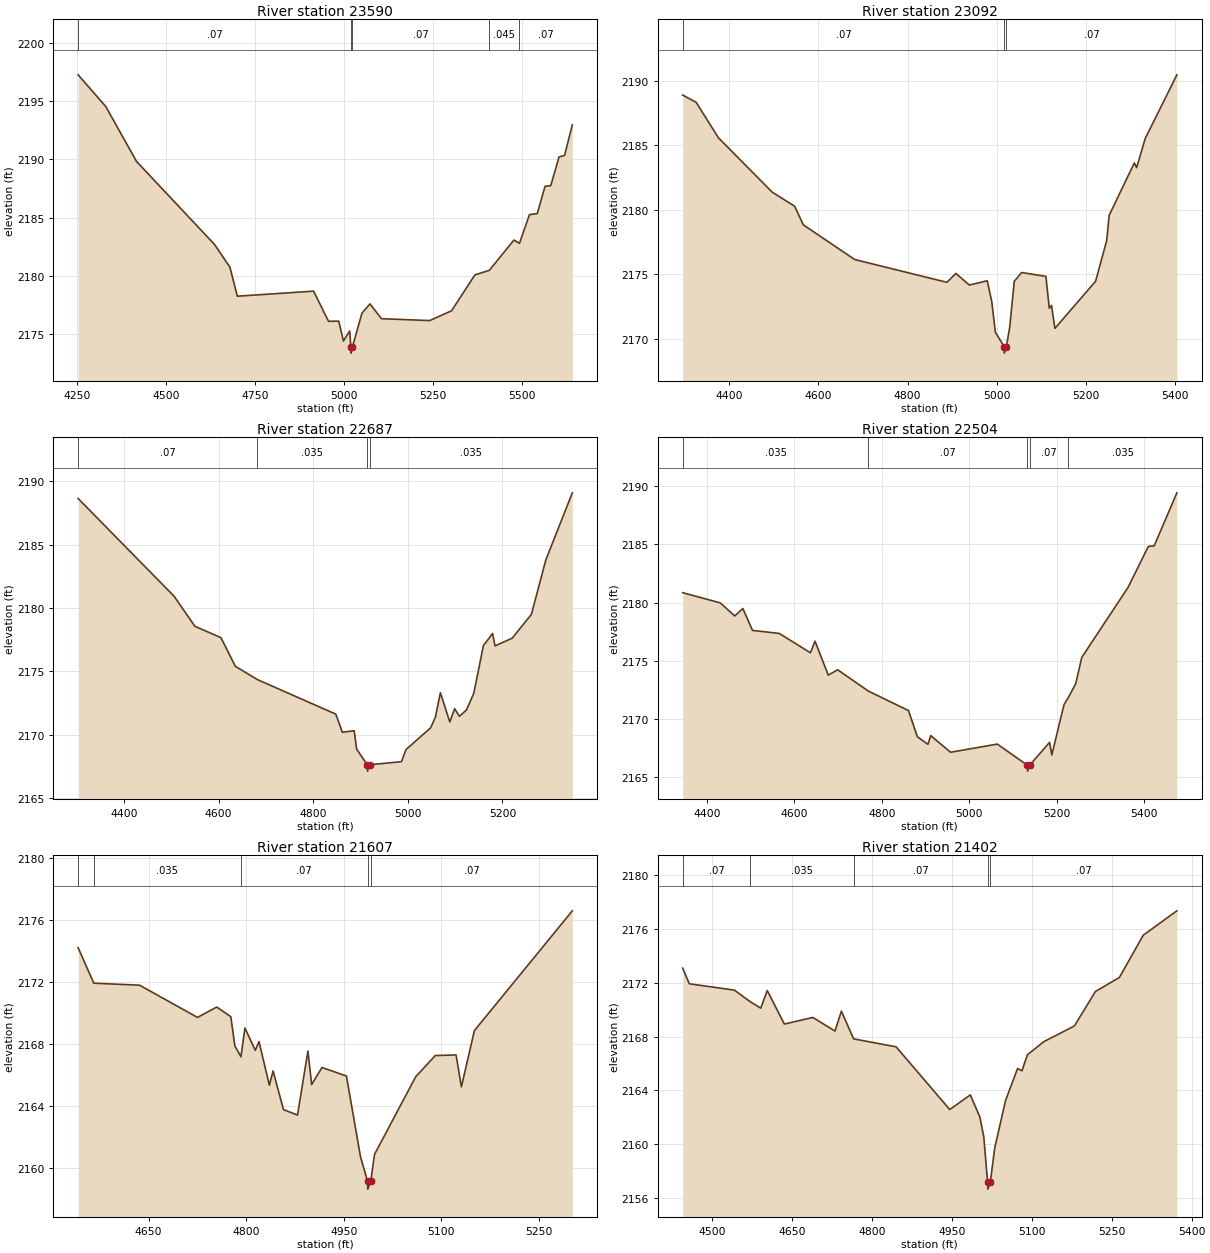
Type RM Length L Ch R = 1,23590,498,498,498
BEGIN DESCRIPTION:
Sweetwater Creek Trib 27 T3 34.0
END DESCRIPTION:
XS GIS Cut Line= 3
      1364855.00      6891388.00      1364391.61      6890801.33
      1363805.00      6890538.00
#Sta/Elev= 30
  4252.4 2197.25  4330.1 2194.54  4416.7 2189.83  4636.3 2182.71  4679.6 2180.76
  4700.4 2178.28  4915.0 2178.71  4956.9 2176.13  4985.8 2176.14  4998.9 2174.44
  5016.5 2175.30  5020.0 2173.90  5020.3 2173.40  5024.0 2173.90  5051.1 2176.83
  5073.8 2177.62  5105.9 2176.35  5241.5 2176.19  5303.2 2177.03  5369.0 2180.11
  5409.3 2180.49  5478.6 2183.09  5494.3 2182.81  5522.4 2185.27  5544.3 2185.36
  5566.3 2187.70  5582.3 2187.75  5605.5 2190.21  5621.1 2190.34  5643.0 2192.96
#Mann=5,-1,0
  4252.4    0.07       0  5020.0    0.07       0  5024.0    0.07       0
  5409.3   0.045       0  5494.3    0.07       0
Bank Sta=5020,5024
Exp/Cntr=0.3,0.1

Type RM Length L Ch R = 1,23092,405,405,405
BEGIN DESCRIPTION:
Sweetwater Creek Trib 27 T3 33.0
END DESCRIPTION:
XS GIS Cut Line= 3
      1364954.95      6890388.00      1364253.67      6890452.07
      1363854.99      6890388.00
#Sta/Elev= 30
  4295.8 2188.90  4325.9 2188.34  4376.1 2185.58  4496.6 2181.37  4546.8 2180.28
  4566.2 2178.84  4681.4 2176.15  4888.2 2174.38  4908.3 2175.07  4938.4 2174.17
  4978.6 2174.50  4988.6 2172.92  4996.8 2170.52  5016.5 2169.39  5016.8 2168.89
  5021.4 2169.39  5029.0 2170.89  5039.2 2174.46  5055.8 2175.14  5110.1 2174.84
  5117.7 2172.37  5122.7 2172.59  5130.3 2170.81  5221.5 2174.46  5246.5 2177.63
  5251.9 2179.57  5308.4 2183.64  5313.5 2183.27  5332.9 2185.54  5403.8 2190.47
#Mann=3,-1,0
  4295.8    0.07       0  5016.5    0.07       0  5021.4    0.07       0
Bank Sta=5016.5,5021.4
Exp/Cntr=0.3,0.1

Type RM Length L Ch R = 1,22687,183,183,183
BEGIN DESCRIPTION:
Sweetwater Creek Trib 27 T3 32.0
END DESCRIPTION:
XS GIS Cut Line= 3
      1364955.01      6890338.00      1364302.42      6890093.74
      1363959.74      6890035.48
#Sta/Elev= 30
  4303.2 2188.65  4506.1 2180.93  4549.9 2178.56  4605.1 2177.66  4635.4 2175.40
  4682.1 2174.35  4847.8 2171.62  4861.6 2170.19  4886.6 2170.31  4891.9 2168.85
  4914.4 2167.62  4914.7 2167.12  4919.3 2167.62  4986.6 2167.87  4996.0 2168.82
  5048.1 2170.54  5058.2 2171.38  5068.8 2173.31  5088.7 2171.00  5098.8 2172.05
  5109.0 2171.45  5124.0 2171.96  5139.4 2173.27  5159.7 2177.04  5179.1 2177.99
  5184.2 2177.01  5220.5 2177.62  5261.1 2179.50  5291.5 2183.79  5347.6 2189.10
#Mann=4,-1,0
  4303.2    0.07       0  4682.1   0.035       0  4914.4   0.035       0
  4919.3   0.035       0
Bank Sta=4914.4,4919.3
Exp/Cntr=0.3,0.1

Type RM Length L Ch R = 1,22504,897,897,897
BEGIN DESCRIPTION:
Sweetwater Creek Trib 27 T3 4040
END DESCRIPTION:
XS GIS Cut Line= 3
      1365091.77      6890119.93      1364448.54      6889994.75
      1363980.68      6889913.83
#Sta/Elev= 30
  4344.7 2180.85  4430.7 2179.97  4463.7 2178.85  4482.3 2179.49  4504.4 2177.61
  4565.5 2177.35  4636.8 2175.69  4647.4 2176.68  4677.6 2173.77  4699.1 2174.23
  4769.3 2172.40  4861.0 2170.73  4881.4 2168.48  4905.6 2167.83  4911.9 2168.58
  4957.3 2167.15  5064.2 2167.85  5133.1 2166.03  5133.4 2165.53  5138.0 2166.03
  5183.7 2168.00  5188.8 2166.92  5216.7 2171.24  5226.0 2171.81  5243.5 2173.04
  5257.3 2175.29  5363.1 2181.30  5409.5 2184.82  5422.9 2184.87  5474.8 2189.42
#Mann=5,-1,0
  4344.7   0.035       0  4769.3    0.07       0  5133.1    0.07       0
  5138.0    0.07       0  5226.0   0.035       0
Bank Sta=5133.1,5138
Exp/Cntr=0.3,0.1

Type RM Length L Ch R = 1,21607,205,205,205
BEGIN DESCRIPTION:
Sweetwater Creek Trib 27 T3 31.0
END DESCRIPTION:
XS GIS Cut Line= 3
      1364954.98      6889837.99      1364555.53      6889613.13
      1364254.95      6889638.00
#Sta/Elev= 30
  4541.6 2174.24  4565.7 2171.95  4636.2 2171.82  4725.2 2169.74  4754.8 2170.41
  4776.4 2169.79  4782.6 2167.91  4792.0 2167.20  4798.1 2169.06  4814.0 2167.62
  4819.8 2168.18  4835.7 2165.36  4841.4 2166.29  4857.4 2163.79  4879.0 2163.44
  4895.0 2167.57  4900.7 2165.41  4916.6 2166.51  4954.2 2165.96  4975.9 2160.74
  4986.7 2159.16  4987.0 2158.66  4991.6 2159.16  4997.4 2160.90  5060.7 2165.91
  5090.8 2167.28  5122.8 2167.32  5131.0 2165.26  5151.0 2168.89  5301.6 2176.62
#Mann=5,-1,0
  4541.6    0.07       0  4565.7   0.035       0  4792.0    0.07       0
  4986.7    0.07       0  4991.6    0.07       0
Bank Sta=4986.7,4991.6
Exp/Cntr=0.3,0.1

Type RM Length L Ch R = 1,21402,293,293,293
BEGIN DESCRIPTION:
Sweetwater Creek Trib 27 T3 4442
END DESCRIPTION:
XS GIS Cut Line= 4
      1365073.24      6889636.89      1364554.43      6889437.78
      1364408.36      6889470.24      1364208.52      6889568.43
#Sta/Elev= 30
  4444.3 2173.08  4456.8 2171.92  4541.5 2171.45  4571.5 2170.58  4590.9 2170.11
  4603.1 2171.42  4635.2 2168.93  4688.8 2169.42  4730.3 2168.41  4742.3 2169.89
  4765.2 2167.83  4845.0 2167.24  4945.8 2162.58  4984.4 2163.67  5002.3 2162.03
  5009.7 2160.55  5016.9 2157.17  5017.3 2156.67  5021.9 2157.17  5030.2 2159.72
  5050.6 2163.26  5073.2 2165.63  5081.4 2165.46  5091.6 2166.65  5122.3 2167.62
  5179.9 2168.79  5219.3 2171.35  5264.3 2172.39  5309.2 2175.53  5372.3 2177.34
#Mann=5,-1,0
  4444.3    0.07       0  4571.5   0.035       0  4765.2    0.07       0
  5016.9    0.07       0  5021.9    0.07       0
Bank Sta=5016.9,5021.9
Exp/Cntr=0.3,0.1

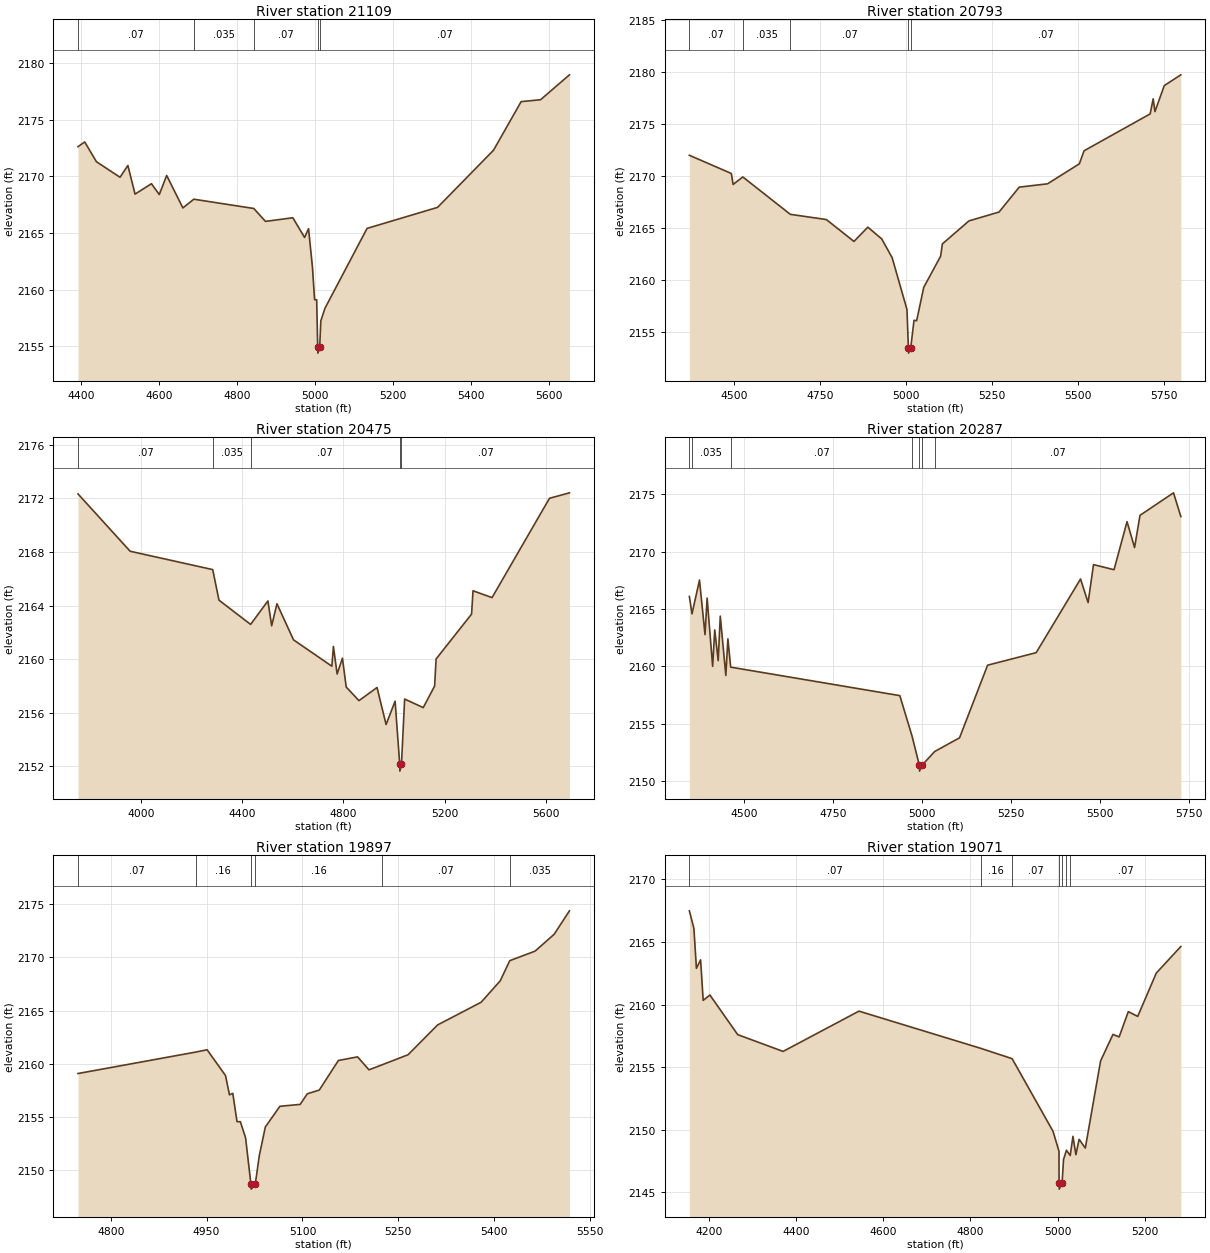
Type RM Length L Ch R = 1,21109,316,316,316
BEGIN DESCRIPTION:
Sweetwater Creek Trib 27 T3 30.0
END DESCRIPTION:
XS GIS Cut Line= 4
      1365292.07      6889164.68      1364689.24      6889239.07
      1364417.04      6889350.45      1364130.57      6889567.47
#Sta/Elev= 30
  4392.6 2172.62  4409.8 2173.04  4440.0 2171.29  4500.5 2169.92  4520.6 2170.96
  4539.0 2168.43  4581.1 2169.35  4601.2 2168.39  4620.1 2170.08  4661.7 2167.21
  4689.7 2167.98  4843.7 2167.16  4873.6 2166.02  4943.8 2166.34  4974.0 2164.60
  4984.1 2165.38  4994.2 2161.95  4999.6 2159.10  5005.0 2159.10  5007.6 2154.88
  5008.0 2154.38  5012.7 2154.88  5015.6 2157.23  5026.2 2158.34  5134.2 2165.40
  5315.2 2167.26  5458.7 2172.31  5529.5 2176.60  5579.4 2176.77  5653.5 2178.97
#Mann=5,-1,0
  4392.6    0.07       0  4689.7   0.035       0  4843.7    0.07       0
  5007.6    0.07       0  5012.7    0.07       0
Bank Sta=5007.6,5012.7
Exp/Cntr=0.3,0.1

Type RM Length L Ch R = 1,20793,318,318,318
BEGIN DESCRIPTION:
Sweetwater Creek Trib 27 T3 4440
END DESCRIPTION:
XS GIS Cut Line= 3
      1365179.21      6889081.35      1364554.85      6888988.00
      1363778.21      6889181.59
#Sta/Elev= 30
  4368.7 2171.99  4491.0 2170.24  4496.1 2169.19  4524.4 2169.91  4662.8 2166.32
  4767.8 2165.82  4848.2 2163.72  4888.6 2165.09  4929.1 2163.96  4959.4 2162.16
  5002.5 2157.20  5006.8 2153.50  5007.3 2153.00  5013.5 2153.50  5023.1 2156.15
  5030.8 2156.11  5051.4 2159.31  5100.6 2162.30  5105.7 2163.48  5183.1 2165.69
  5270.8 2166.54  5329.6 2168.93  5412.1 2169.25  5504.8 2171.17  5518.5 2172.42
  5711.0 2175.96  5719.8 2177.41  5725.0 2176.18  5752.2 2178.68  5800.4 2179.71
#Mann=5,-1,0
  4368.7    0.07       0  4524.4   0.035       0  4662.8    0.07       0
  5006.8    0.07       0  5013.5    0.07       0
Bank Sta=5006.8,5013.5
Exp/Cntr=0.3,0.1

Type RM Length L Ch R = 1,20475,188,188,188
BEGIN DESCRIPTION:
Sweetwater Creek Trib 27 T3 29.0
END DESCRIPTION:
XS GIS Cut Line= 3
      1365673.70      6887980.94      1364655.45      6888701.82
      1364052.35      6889042.36
#Sta/Elev= 30
  3752.4 2172.34  3958.3 2168.06  4284.3 2166.69  4309.0 2164.41  4433.9 2162.60
  4502.2 2164.35  4517.0 2162.50  4537.9 2164.14  4603.2 2161.45  4754.6 2159.48
  4760.7 2160.95  4775.5 2158.90  4796.4 2160.08  4811.2 2157.93  4861.6 2156.91
  4933.0 2157.89  4968.7 2155.13  5004.3 2156.87  5022.6 2152.15  5023.1 2151.65
  5029.4 2152.15  5041.9 2157.03  5115.4 2156.39  5160.3 2158.00  5166.1 2160.02
  5306.2 2163.37  5311.9 2165.11  5387.0 2164.60  5613.7 2172.01  5692.6 2172.42
#Mann=5,-1,0
  3752.4    0.07       0  4284.3   0.035       0  4433.9    0.07       0
  5022.6    0.07       0  5029.4    0.07       0
Bank Sta=5022.6,5029.4
Exp/Cntr=0.3,0.1

Type RM Length L Ch R = 1,20287,390,390,390
BEGIN DESCRIPTION:
Sweetwater Creek Trib 27 T3 28.0
END DESCRIPTION:
XS GIS Cut Line= 3
      1365215.43      6888179.08      1364655.05      6888514.31
      1364042.48      6888903.96
#Sta/Elev= 30
  4347.0 2166.09  4354.4 2164.58  4375.4 2167.52  4390.9 2162.77  4396.8 2165.95
  4412.3 2160.01  4418.2 2163.18  4427.9 2160.51  4433.7 2164.38  4449.3 2159.22
  4455.1 2162.40  4462.9 2159.94  4937.5 2157.46  4971.8 2153.94  4992.4 2151.39
  4992.9 2150.89  4999.3 2151.39  5035.4 2152.60  5105.1 2153.79  5183.8 2160.11
  5320.1 2161.20  5444.6 2167.61  5465.8 2165.56  5481.0 2168.86  5538.6 2168.42
  5575.0 2172.60  5596.2 2170.35  5611.4 2173.15  5705.4 2175.11  5726.0 2173.05
#Mann=7,-1,0
  4347.0    0.07       0  4354.4   0.035       0  4462.9    0.07       0
  4971.8    0.16       0  4992.4    0.07       0  4999.3    0.16       0
  5035.4    0.07       0
Bank Sta=4992.4,4999.3
Exp/Cntr=0.3,0.1

Type RM Length L Ch R = 1,19897,826,826,826
BEGIN DESCRIPTION:
Sweetwater Creek Trib 27 T3 4039
END DESCRIPTION:
XS GIS Cut Line= 3
      1364898.08      6888091.87      1364655.30      6888156.38
      1364172.61      6888343.53
#Sta/Elev= 30
  4748.8 2159.06  4932.8 2161.08  4950.8 2161.30  4979.6 2158.87  4985.8 2157.05
  4991.0 2157.19  4997.6 2154.52  5002.8 2154.52  5011.0 2153.00  5019.3 2148.66
  5019.8 2148.16  5026.2 2148.66  5032.5 2151.33  5041.9 2154.02  5064.7 2155.97
  5096.4 2156.15  5107.6 2157.15  5126.3 2157.50  5156.2 2160.29  5186.2 2160.63
  5204.1 2159.41  5224.9 2159.89  5265.2 2160.83  5311.4 2163.64  5379.5 2165.78
  5409.4 2167.80  5424.3 2169.70  5463.9 2170.60  5493.8 2172.19  5517.7 2174.40
#Mann=6,-1,0
  4748.8    0.07       0  4932.8    0.16       0  5019.3    0.07       0
  5026.2    0.16       0  5224.9    0.07       0  5424.3   0.035       0
Bank Sta=5019.3,5026.2
Exp/Cntr=0.3,0.1

Type RM Length L Ch R = 1,19071,438,438,438
BEGIN DESCRIPTION:
Sweetwater Creek Trib 27 T3 27.0
END DESCRIPTION:
XS GIS Cut Line= 4
      1365228.76      6888178.46      1364818.58      6887926.74
      1364714.85      6887577.89      1364505.01      6887388.01
#Sta/Elev= 30
  4154.8 2167.49  4165.2 2166.09  4171.0 2162.89  4180.6 2163.57  4186.5 2160.33
  4201.9 2160.76  4265.8 2157.59  4370.0 2156.25  4544.1 2159.47  4823.3 2156.50
  4895.7 2155.67  4989.5 2149.87  5003.3 2148.27  5003.4 2145.74  5003.9 2145.24
  5010.4 2145.74  5013.7 2147.61  5020.5 2148.35  5029.1 2147.93  5035.3 2149.46
  5042.1 2147.99  5049.5 2149.22  5063.7 2148.52  5098.8 2155.49  5127.2 2157.61
  5141.4 2157.41  5162.4 2159.43  5184.0 2159.05  5226.6 2162.51  5283.0 2164.64
#Mann=7,-1,0
  4154.8    0.07       0  4823.3    0.16       0  4895.7    0.07       0
  5003.4    0.07       0  5010.4    0.07       0  5020.5    0.16       0
  5029.1    0.07       0
Bank Sta=5003.4,5010.4
Exp/Cntr=0.3,0.1

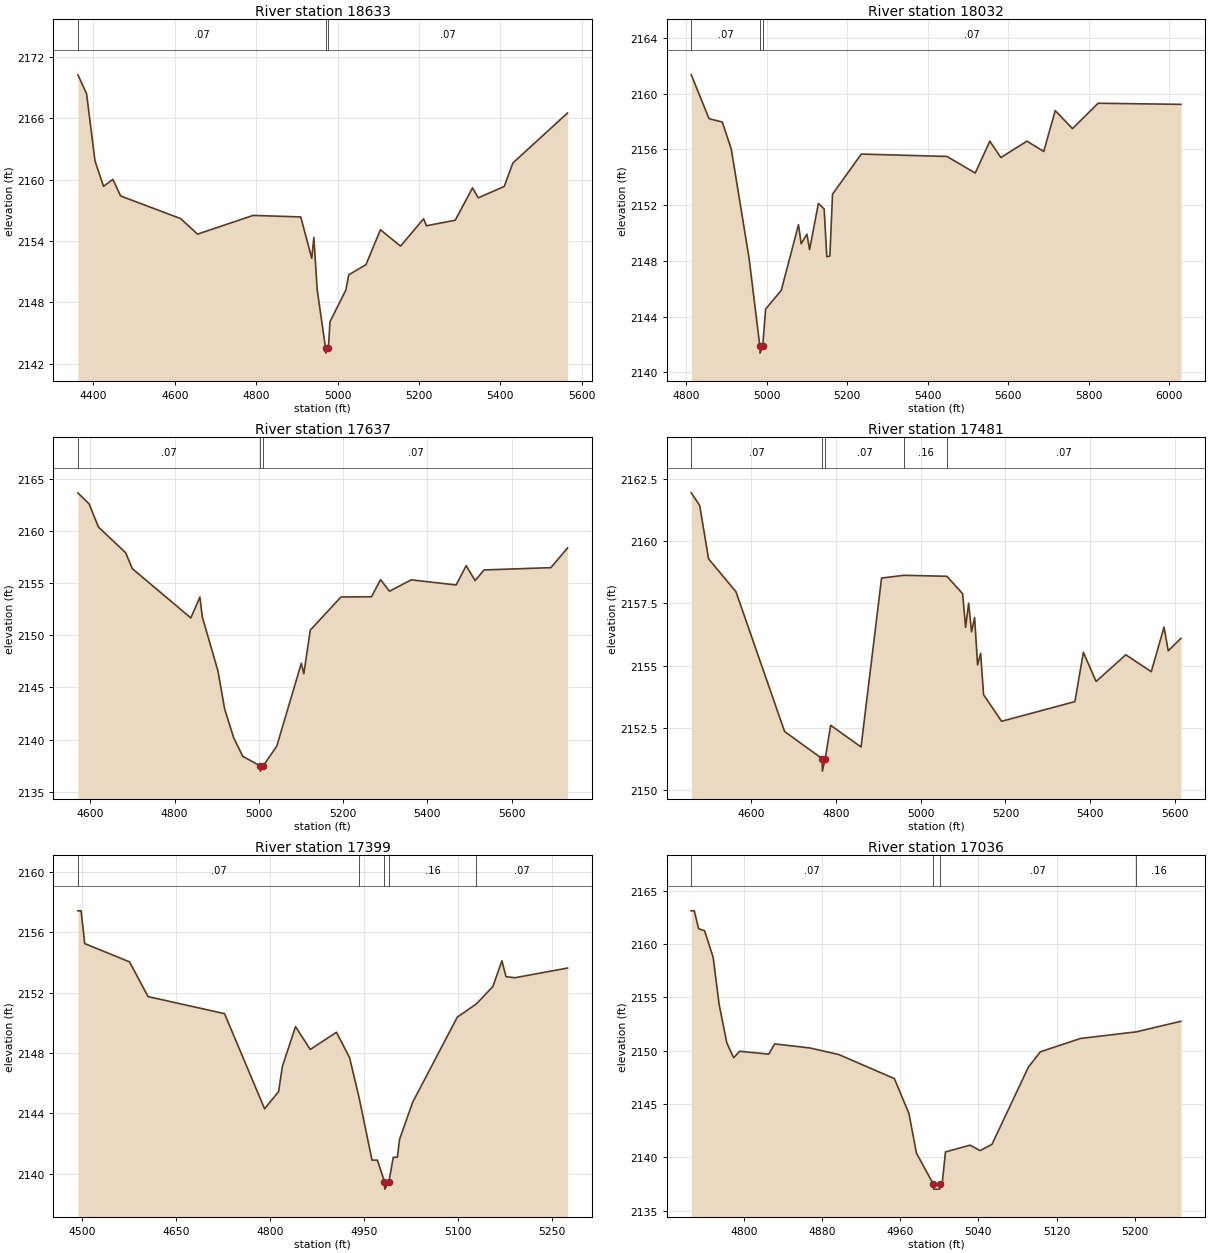
Type RM Length L Ch R = 1,18633,601,601,601
BEGIN DESCRIPTION:
Sweetwater Creek Trib 27 T3 26.0
END DESCRIPTION:
XS GIS Cut Line= 3
      1365255.01      6888188.03      1365061.47      6887580.31
      1364655.01      6887188.01
#Sta/Elev= 30
  4362.2 2170.24  4383.6 2168.38  4404.2 2161.83  4425.2 2159.34  4448.0 2160.02
  4467.2 2158.40  4614.4 2156.19  4656.1 2154.67  4792.5 2156.50  4909.6 2156.35
  4936.6 2152.31  4941.8 2154.35  4949.9 2149.25  4970.5 2143.54  4971.0 2143.04
  4977.5 2143.54  4981.4 2146.11  5020.4 2149.21  5027.4 2150.69  5069.8 2151.69
  5105.3 2155.10  5154.7 2153.50  5211.3 2156.17  5218.3 2155.49  5289.0 2156.03
  5331.5 2159.19  5345.6 2158.22  5409.4 2159.33  5430.5 2161.62  5564.9 2166.51
#Mann=3,-1,0
  4362.2    0.07       0  4970.5    0.07       0  4977.5    0.07       0
Bank Sta=4970.5,4977.5
Exp/Cntr=0.3,0.1

Type RM Length L Ch R = 1,18032,395,395,395
BEGIN DESCRIPTION:
Sweetwater Creek Trib 27 T3 25.0
END DESCRIPTION:
XS GIS Cut Line= 3
      1365554.99      6887787.98      1365475.58      6887618.79
      1364805.02      6886838.02
#Sta/Elev= 30
  4813.1 2161.36  4857.3 2158.21  4890.2 2157.97  4912.5 2156.02  4956.7 2148.19
  4983.4 2141.88  4983.9 2141.38  4990.5 2141.88  4997.7 2144.54  5036.6 2145.89
  5079.4 2150.60  5086.0 2149.23  5100.3 2149.92  5106.9 2148.81  5128.8 2152.13
  5143.1 2151.73  5149.7 2148.30  5157.3 2148.35  5163.9 2152.79  5235.3 2155.67
  5448.1 2155.50  5518.4 2154.31  5554.6 2156.60  5582.0 2155.42  5646.8 2156.60
  5688.5 2155.86  5717.0 2158.79  5759.8 2157.50  5823.5 2159.32  6029.2 2159.24
#Mann=3,-1,0
  4813.1    0.07       0  4983.4    0.07       0  4990.5    0.07       0
Bank Sta=4983.4,4990.5
Exp/Cntr=0.3,0.1

Type RM Length L Ch R = 1,17637,156,156,156
BEGIN DESCRIPTION:
Sweetwater Creek Trib 27 T3 24.0
END DESCRIPTION:
XS GIS Cut Line= 3
      1365816.89      6887651.16      1365600.96      6887279.65
      1364981.53      6886887.55
#Sta/Elev= 30
  4570.3 2163.65  4597.1 2162.58  4619.1 2160.37  4683.7 2157.91  4699.4 2156.39
  4838.5 2151.66  4860.0 2153.66  4865.8 2151.75  4903.0 2146.57  4918.7 2142.95
  4940.3 2140.17  4961.8 2138.40  5003.2 2137.48  5003.7 2136.98  5010.3 2137.48
  5042.6 2139.38  5100.9 2147.32  5106.8 2146.31  5122.1 2150.49  5195.0 2153.67
  5267.4 2153.69  5289.0 2155.33  5310.2 2154.22  5361.9 2155.31  5468.6 2154.82
  5492.3 2156.67  5513.6 2155.24  5534.8 2156.26  5693.5 2156.48  5733.1 2158.37
#Mann=3,-1,0
  4570.3    0.07       0  5003.2    0.07       0  5010.3    0.07       0
Bank Sta=5003.2,5010.3
Exp/Cntr=0.3,0.1

Type RM Length L Ch R = 1,17481,82,82,82
BEGIN DESCRIPTION:
Sweetwater Creek Trib 27 T3 4157
END DESCRIPTION:
XS GIS Cut Line= 6
      1365901.68      6887599.29      1365742.61      6887386.02
      1365774.94      6887306.85      1365776.24      6887240.45
      1365504.11      6886978.73      1365145.08      6886991.10
#Sta/Elev= 30
  4459.1 2161.94  4479.0 2161.43  4499.9 2159.29  4564.5 2157.97  4679.2 2152.36
  4767.8 2151.27  4768.3 2150.77  4775.0 2151.27  4787.8 2152.61  4859.5 2151.74
  4907.9 2158.52  4960.9 2158.63  5061.9 2158.59  5099.1 2157.89  5106.0 2156.54
  5113.2 2157.51  5120.1 2156.36  5127.3 2156.94  5134.3 2155.03  5141.5 2155.50
  5148.4 2153.84  5190.9 2152.77  5363.8 2153.56  5383.8 2155.54  5413.9 2154.37
  5483.9 2155.44  5543.9 2154.76  5574.0 2156.55  5584.0 2155.60  5613.9 2156.10
#Mann=5,-1,0
  4459.1    0.07       0  4767.8    0.07       0  4775.0    0.07       0
  4960.9    0.16       0  5061.9    0.07       0
Bank Sta=4767.8,4775
Exp/Cntr=0.3,0.1

Type RM Length L Ch R = 1,17399,363,363,363
BEGIN DESCRIPTION:
Sweetwater Creek Trib 27 T3 4158
END DESCRIPTION:
XS GIS Cut Line= 3
      1366036.68      6887511.30      1365745.00      6887097.71
      1365539.64      6886915.26
#Sta/Elev= 30
  4493.9 2157.42  4499.0 2157.42  4504.8 2155.25  4576.2 2154.04  4605.8 2151.74
  4727.7 2150.61  4791.6 2144.31  4813.9 2145.45  4820.0 2147.12  4840.9 2149.75
  4864.4 2148.24  4906.2 2149.38  4927.1 2147.70  4942.3 2145.05  4962.9 2140.91
  4971.5 2140.91  4982.7 2139.49  4983.2 2138.99  4989.9 2139.49  4996.8 2141.10
  5003.3 2141.10  5006.9 2142.30  5027.8 2144.75  5098.9 2150.38  5129.1 2151.25
  5155.7 2152.41  5170.0 2154.11  5176.6 2153.06  5190.9 2152.99  5274.7 2153.63
#Mann=5,-1,0
  4493.9    0.07       0  4942.3    0.16       0  4982.7    0.07       0
  4989.9    0.16       0  5129.1    0.07       0
Bank Sta=4982.7,4989.9
Exp/Cntr=0.3,0.1

Type RM Length L Ch R = 1,17036,379,379,379
BEGIN DESCRIPTION:
Sweetwater Creek Trib 27 T3 23.0
END DESCRIPTION:
XS GIS Cut Line= 3
      1366155.03      6887438.04      1366011.59      6887228.78
      1365955.01      6886988.04
#Sta/Elev= 30
  4746.3 2163.10  4749.4 2163.10  4753.8 2161.42  4759.9 2161.24  4768.7 2158.74
  4774.8 2154.33  4782.7 2150.71  4789.7 2149.33  4795.7 2149.94  4825.5 2149.67
  4831.6 2150.63  4867.6 2150.25  4897.3 2149.63  4954.1 2147.38  4969.0 2144.11
  4976.7 2140.39  4993.8 2137.52  4994.3 2137.02  5000.5 2137.02  5001.0 2137.52
  5003.0 2137.52  5006.4 2140.51  5031.6 2141.14  5041.9 2140.63  5054.0 2141.22
  5091.2 2148.45  5103.5 2149.89  5144.6 2151.14  5201.7 2151.76  5247.3 2152.75
#Mann=4,-1,0
  4746.3    0.07       0  4993.8    0.07       0  5001.0    0.07       0
  5201.7    0.16       0
Bank Sta=4993.8,5001
Exp/Cntr=0.3,0.1

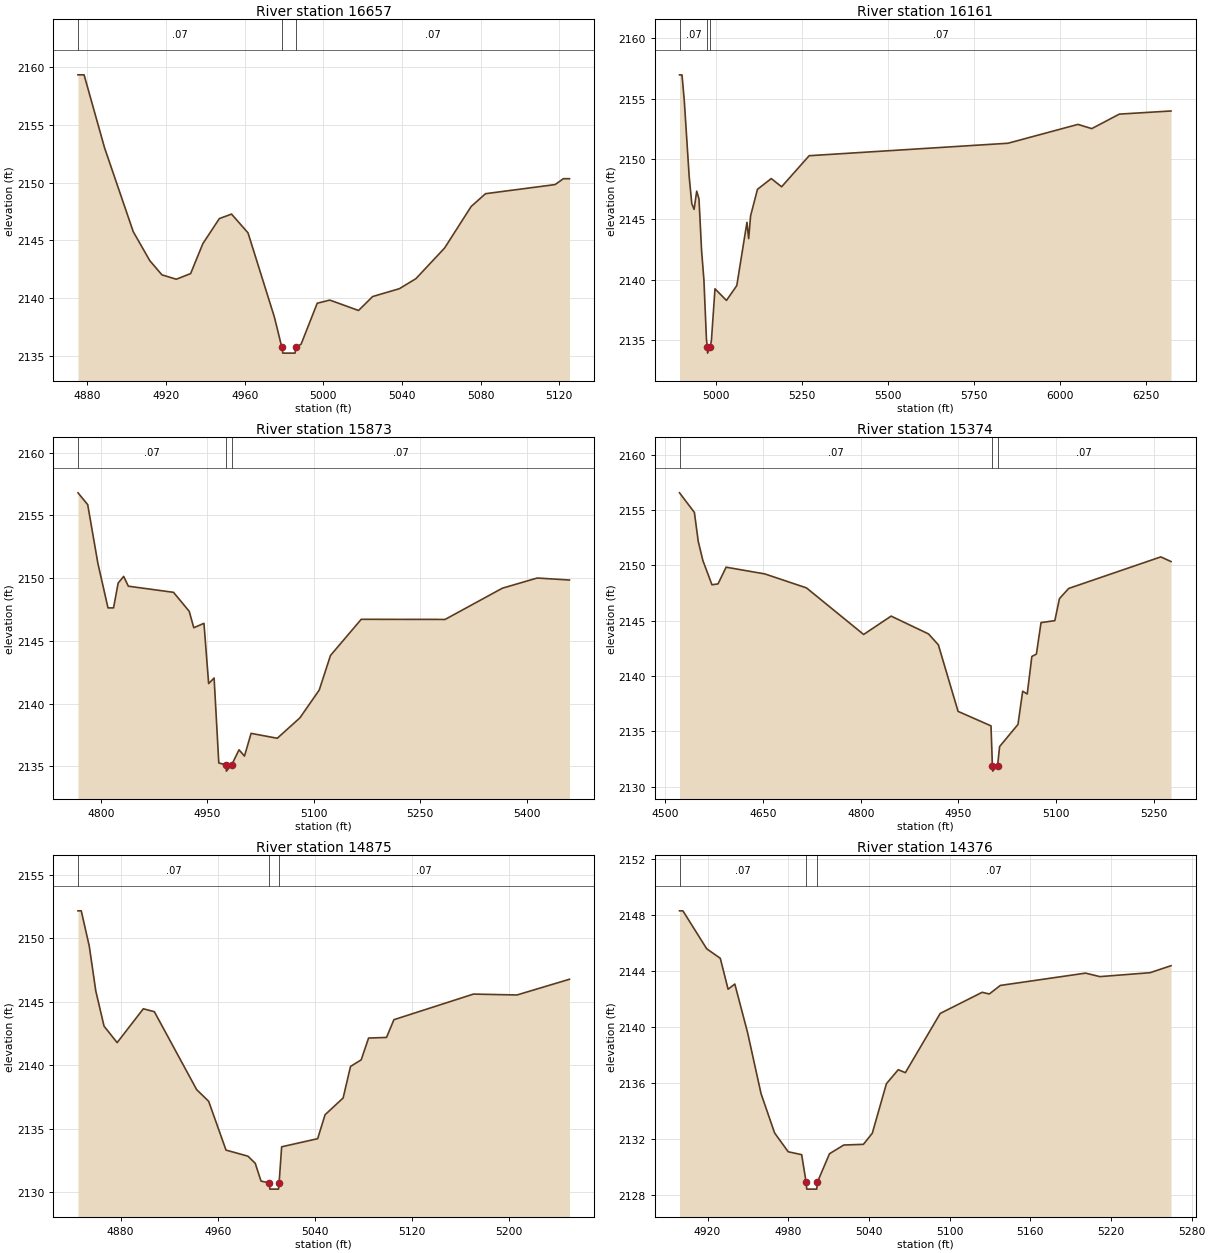
Type RM Length L Ch R = 1,16657,496,496,496
BEGIN DESCRIPTION:
Sweetwater Creek Trib 27 T3 22.0
END DESCRIPTION:
XS GIS Cut Line= 3
      1366404.99      6887187.99      1366330.19      6887088.09
      1366254.99      6886987.99
#Sta/Elev= 30
  4875.2 2159.35  4878.3 2159.35  4888.7 2153.03  4903.3 2145.75  4911.7 2143.24
  4917.9 2142.00  4925.2 2141.62  4932.5 2142.11  4938.7 2144.70  4947.1 2146.88
  4953.3 2147.27  4961.7 2145.64  4975.1 2138.34  4978.9 2135.71  4979.4 2135.21
  4985.6 2135.21  4986.1 2135.71  4988.7 2135.99  4996.9 2139.54  5003.3 2139.81
  5017.9 2138.91  5025.1 2140.12  5038.7 2140.80  5047.1 2141.67  5061.7 2144.33
  5075.2 2147.93  5082.5 2149.04  5117.9 2149.83  5122.1 2150.34  5125.2 2150.34
#Mann=3,-1,0
  4875.2    0.07       0  4978.9    0.07       0  4986.1    0.07       0
Bank Sta=4978.9,4986.1
Exp/Cntr=0.3,0.1

Type RM Length L Ch R = 1,16161,288,288,288
BEGIN DESCRIPTION:
Sweetwater Creek Trib 27 T3 21.0
END DESCRIPTION:
XS GIS Cut Line= 3
      1366755.03      6886838.03      1366675.04      6886768.02
      1365355.00      6886838.00
#Sta/Elev= 30
  4893.7 2156.96  4900.9 2156.95  4907.5 2154.83  4921.7 2148.55  4929.3 2146.30
  4936.0 2145.83  4943.6 2147.34  4950.2 2146.70  4957.8 2142.41  4964.5 2140.01
  4972.0 2135.03  4974.7 2134.44  4975.2 2133.94  4982.6 2134.44  4986.3 2134.97
  4996.7 2139.26  5030.1 2138.30  5060.1 2139.53  5089.6 2144.76  5094.6 2143.41
  5100.2 2145.30  5120.2 2147.49  5160.3 2148.38  5190.3 2147.70  5270.4 2150.27
  5848.0 2151.30  6051.5 2152.86  6091.6 2152.51  6171.7 2153.71  6321.9 2153.97
#Mann=3,-1,0
  4893.7    0.07       0  4974.7    0.07       0  4982.6    0.07       0
Bank Sta=4974.7,4982.6
Exp/Cntr=0.3,0.1

Type RM Length L Ch R = 1,15873,499,499,499
BEGIN DESCRIPTION:
Sweetwater Creek Trib 27 T3 20.0
END DESCRIPTION:
XS GIS Cut Line= 3
      1366905.03      6886688.04      1366755.20      6886510.64
      1366354.98      6886738.01
#Sta/Elev= 30
  4767.8 2156.80  4781.5 2155.86  4795.8 2151.19  4810.1 2147.63  4817.9 2147.63
  4824.4 2149.61  4832.2 2150.14  4838.7 2149.36  4902.4 2148.87  4924.5 2147.36
  4931.0 2146.05  4945.3 2146.40  4951.9 2141.60  4959.6 2142.04  4966.2 2135.27
  4976.4 2135.12  4976.9 2134.62  4984.4 2135.12  4994.7 2136.32  5002.4 2135.82
  5011.7 2137.63  5048.6 2137.24  5080.4 2138.86  5107.7 2141.08  5123.6 2143.84
  5166.9 2146.72  5285.1 2146.71  5365.8 2149.20  5414.8 2150.01  5460.3 2149.85
#Mann=3,-1,0
  4767.8    0.07       0  4976.4    0.07       0  4984.4    0.07       0
Bank Sta=4976.4,4984.4
Exp/Cntr=0.3,0.1

Type RM Length L Ch R = 1,15374,499,499,499
BEGIN DESCRIPTION:
Sweetwater Creek Trib 27 T3 19.0
END DESCRIPTION:
XS GIS Cut Line= 3
      1367005.02      6886588.03      1366745.19      6886186.46
      1366550.77      6885990.00
#Sta/Elev= 30
  4521.7 2156.56  4544.5 2154.79  4550.4 2152.18  4557.5 2150.45  4571.5 2148.25
  4580.8 2148.33  4593.2 2149.84  4652.8 2149.23  4716.6 2147.97  4804.4 2143.76
  4846.6 2145.42  4904.0 2143.81  4919.1 2142.83  4949.4 2136.81  5000.0 2135.50
  5002.1 2131.91  5002.6 2131.41  5010.1 2131.91  5013.2 2133.63  5041.4 2135.63
  5048.6 2138.63  5055.6 2138.38  5062.7 2141.77  5069.7 2141.99  5076.8 2144.83
  5098.0 2145.01  5105.1 2147.00  5119.3 2147.92  5260.7 2150.77  5276.4 2150.35
#Mann=3,-1,0
  4521.7    0.07       0  5002.1    0.07       0  5010.1    0.07       0
Bank Sta=5002.1,5010.1
Exp/Cntr=0.3,0.1

Type RM Length L Ch R = 1,14875,499,499,499
BEGIN DESCRIPTION:
Sweetwater Creek Trib 27 T3 18.0
END DESCRIPTION:
XS GIS Cut Line= 3
      1367354.96      6886137.98      1367211.06      6886079.86
      1367004.97      6885937.98
#Sta/Elev= 30
  4844.8 2152.18  4847.5 2152.18  4854.1 2149.40  4859.5 2145.85  4866.3 2143.08
  4877.1 2141.78  4898.7 2144.45  4907.8 2144.22  4942.7 2138.07  4952.6 2137.15
  4966.9 2133.30  4985.0 2132.82  4991.0 2132.26  4995.8 2130.85  5002.6 2130.72
  5003.1 2130.22  5010.2 2130.22  5010.7 2130.72  5012.8 2133.56  5042.5 2134.20
  5048.6 2136.09  5063.5 2137.41  5069.6 2139.90  5078.4 2140.42  5084.5 2142.14
  5099.3 2142.19  5105.4 2143.59  5171.0 2145.61  5206.9 2145.54  5250.2 2146.78
#Mann=3,-1,0
  4844.8    0.07       0  5002.6    0.07       0  5010.7    0.07       0
Bank Sta=5002.6,5010.7
Exp/Cntr=0.3,0.1

Type RM Length L Ch R = 1,14376,493,493,493
BEGIN DESCRIPTION:
Sweetwater Creek Trib 27 T3 17.0
END DESCRIPTION:
XS GIS Cut Line= 3
      1367605.01      6885688.00      1367505.14      6885701.69
      1367255.01      6885788.00
#Sta/Elev= 30
  4899.2 2148.27  4901.7 2148.27  4919.4 2145.56  4929.5 2144.88  4935.3 2142.67
  4940.3 2143.04  4949.7 2139.61  4959.8 2135.21  4969.9 2132.40  4980.0 2131.06
  4990.0 2130.85  4993.3 2128.89  4993.8 2128.39  5001.2 2128.39  5001.7 2128.89
  5010.7 2130.92  5021.3 2131.54  5035.9 2131.59  5042.5 2132.38  5053.0 2135.92
  5061.8 2136.92  5067.1 2136.71  5093.0 2140.94  5124.2 2142.45  5129.5 2142.33
  5137.7 2142.94  5201.1 2143.82  5211.7 2143.57  5249.0 2143.85  5264.6 2144.35
#Mann=3,-1,0
  4899.2    0.07       0  4993.3    0.07       0  5001.7    0.07       0
Bank Sta=4993.3,5001.7
Exp/Cntr=0.3,0.1

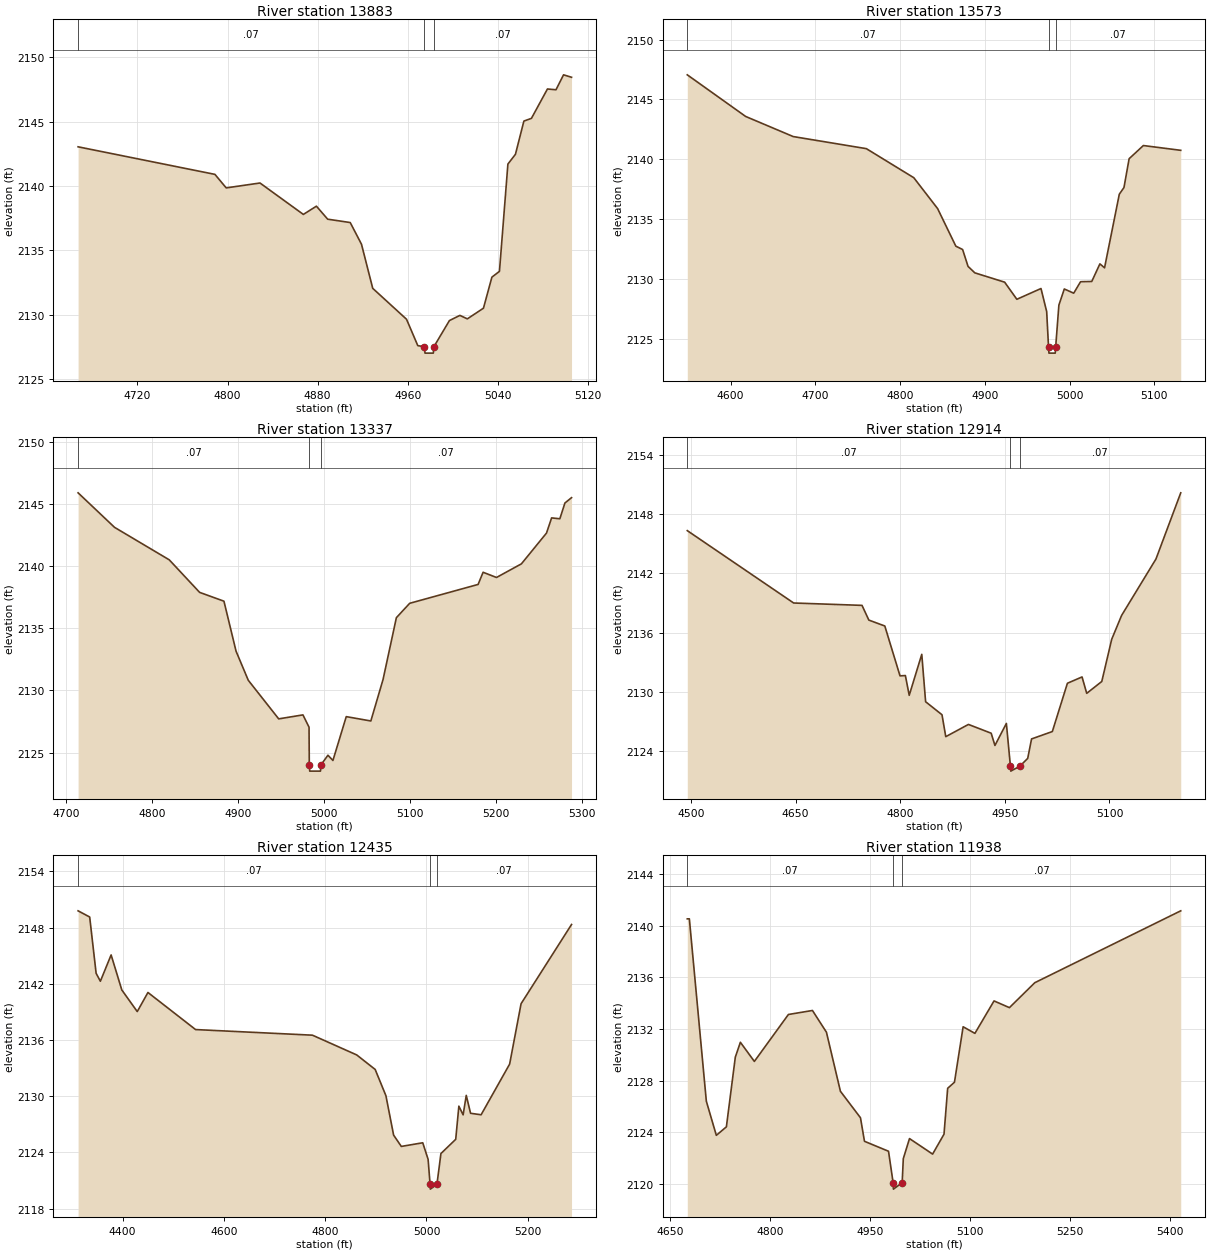
Type RM Length L Ch R = 1,13883,310,310,310
BEGIN DESCRIPTION:
Sweetwater Creek Trib 27 T3 16.0
END DESCRIPTION:
XS GIS Cut Line= 3
      1367616.40      6885304.77      1367283.97      6885318.23
      1367204.99      6885388.01
#Sta/Elev= 30
  4667.3 2143.05  4788.8 2140.91  4798.8 2139.86  4828.8 2140.24  4867.3 2137.80
  4878.9 2138.44  4888.9 2137.43  4908.9 2137.17  4918.9 2135.49  4928.9 2132.06
  4958.9 2129.66  4968.9 2127.61  4974.8 2127.53  4975.3 2127.03  4982.7 2127.03
  4983.2 2127.53  4997.0 2129.56  5006.3 2129.96  5012.9 2129.69  5027.2 2130.52
  5034.7 2132.93  5041.4 2133.38  5048.9 2141.71  5055.6 2142.47  5063.1 2145.05
  5069.8 2145.26  5084.0 2147.54  5091.6 2147.48  5098.3 2148.64  5105.4 2148.45
#Mann=3,-1,0
  4667.3    0.07       0  4974.8    0.07       0  4983.2    0.07       0
Bank Sta=4974.8,4983.2
Exp/Cntr=0.3,0.1

Type RM Length L Ch R = 1,13573,236,236,236
BEGIN DESCRIPTION:
Sweetwater Creek Trib 27 T3 4174
END DESCRIPTION:
XS GIS Cut Line= 3
      1367710.14      6885329.10      1367358.66      6885046.18
      1367239.83      6885101.55
#Sta/Elev= 30
  4548.8 2147.05  4617.7 2143.57  4673.8 2141.89  4760.1 2140.88  4816.1 2138.45
  4844.2 2135.87  4865.7 2132.73  4873.7 2132.45  4880.1 2131.04  4888.1 2130.50
  4923.3 2129.72  4937.7 2128.29  4966.2 2129.19  4972.9 2127.26  4975.1 2124.29
  4975.6 2123.79  4983.0 2123.79  4983.5 2124.29  4987.3 2127.80  4993.7 2129.15
  5004.8 2128.80  5012.9 2129.76  5026.1 2129.78  5035.7 2131.25  5041.2 2130.92
  5058.6 2137.07  5064.1 2137.63  5070.2 2140.04  5087.0 2141.14  5131.1 2140.74
#Mann=3,-1,0
  4548.8    0.07       0  4975.1    0.07       0  4983.5    0.07       0
Bank Sta=4975.1,4983.5
Exp/Cntr=0.3,0.1

Type RM Length L Ch R = 1,13337,423,423,423
BEGIN DESCRIPTION:
Sweetwater Creek Trib 27 T3 15.0
END DESCRIPTION:
XS GIS Cut Line= 3
      1367755.00      6885138.00      1367553.56      6884934.42
      1367405.02      6884688.03
#Sta/Elev= 30
  4713.6 2145.92  4756.0 2143.14  4819.7 2140.52  4855.0 2137.90  4883.3 2137.19
  4897.4 2133.16  4911.6 2130.82  4947.0 2127.71  4975.2 2128.03  4982.3 2127.04
  4982.6 2124.00  4983.1 2123.50  4995.6 2123.50  4996.1 2124.00  5004.3 2124.78
  5010.1 2124.36  5025.6 2127.89  5054.2 2127.54  5068.4 2130.88  5083.9 2135.86
  5099.4 2137.02  5179.0 2138.54  5184.8 2139.52  5200.4 2139.10  5229.4 2140.20
  5258.6 2142.68  5264.5 2143.90  5274.1 2143.83  5280.0 2145.10  5287.7 2145.53
#Mann=3,-1,0
  4713.6    0.07       0  4982.6    0.07       0  4996.1    0.07       0
Bank Sta=4982.6,4996.1
Exp/Cntr=0.3,0.1

Type RM Length L Ch R = 1,12914,479,479,479
BEGIN DESCRIPTION:
Sweetwater Creek Trib 27 T3 14.0
END DESCRIPTION:
XS GIS Cut Line= 3
      1367854.99      6885037.98      1367654.50      6884574.16
      1367505.01      6884438.01
#Sta/Elev= 30
  4494.7 2146.34  4647.2 2139.01  4745.2 2138.77  4755.0 2137.28  4777.9 2136.68
  4799.7 2131.63  4807.4 2131.66  4812.9 2129.66  4830.9 2133.81  4836.4 2129.01
  4859.9 2127.69  4865.3 2125.47  4897.8 2126.71  4930.4 2125.82  4935.8 2124.58
  4952.2 2126.81  4958.0 2122.48  4958.5 2121.98  4971.5 2122.48  4982.8 2123.27
  4988.3 2125.24  5018.1 2125.99  5039.7 2130.88  5060.7 2131.52  5067.4 2129.86
  5089.0 2131.06  5103.2 2135.33  5117.4 2137.75  5166.7 2143.47  5202.2 2150.17
#Mann=3,-1,0
  4494.7    0.07       0  4958.0    0.07       0  4971.5    0.07       0
Bank Sta=4958,4971.5
Exp/Cntr=0.3,0.1

Type RM Length L Ch R = 1,12435,497,497,497
BEGIN DESCRIPTION:
Sweetwater Creek Trib 27 T3 13.0
END DESCRIPTION:
XS GIS Cut Line= 3
      1368405.01      6884938.01      1368035.11      6884358.27
      1367804.96      6884187.97
#Sta/Elev= 30
  4312.3 2149.80  4335.2 2149.14  4347.9 2143.13  4356.3 2142.28  4377.5 2145.09
  4398.6 2141.35  4429.1 2139.04  4450.2 2141.08  4544.2 2137.12  4774.9 2136.52
  4862.3 2134.41  4898.7 2132.86  4919.9 2130.06  4935.1 2125.85  4950.3 2124.64
  4992.6 2125.03  5003.2 2123.26  5007.1 2120.58  5007.6 2120.08  5020.6 2120.58
  5028.5 2123.88  5057.7 2125.40  5063.9 2128.94  5072.3 2128.01  5078.5 2130.09
  5087.0 2128.18  5107.8 2128.02  5164.1 2133.43  5186.7 2139.88  5286.3 2148.34
#Mann=3,-1,0
  4312.3    0.07       0  5007.1    0.07       0  5020.6    0.07       0
Bank Sta=5007.1,5020.6
Exp/Cntr=0.3,0.1

Type RM Length L Ch R = 1,11938,500,500,500
BEGIN DESCRIPTION:
Sweetwater Creek Trib 27 T3 12.0
END DESCRIPTION:
XS GIS Cut Line= 3
      1368755.04      6884388.03      1368485.11      6884208.28
      1368105.01      6884038.00
#Sta/Elev= 30
  4675.7 2140.52  4678.8 2140.52  4704.3 2126.41  4719.3 2123.77  4734.4 2124.43
  4747.8 2129.82  4755.4 2130.97  4776.4 2129.49  4827.5 2133.12  4863.6 2133.43
  4884.6 2131.75  4905.6 2127.18  4935.7 2125.13  4941.7 2123.31  4977.8 2122.54
  4984.7 2120.11  4985.2 2119.61  4998.3 2120.11  5000.0 2121.97  5009.3 2123.52
  5044.0 2122.32  5061.1 2123.86  5066.6 2127.41  5076.8 2127.88  5089.8 2132.17
  5107.5 2131.66  5136.2 2134.17  5159.3 2133.65  5197.4 2135.58  5416.5 2141.14
#Mann=3,-1,0
  4675.7    0.07       0  4984.7    0.07       0  4998.3    0.07       0
Bank Sta=4984.7,4998.3
Exp/Cntr=0.3,0.1