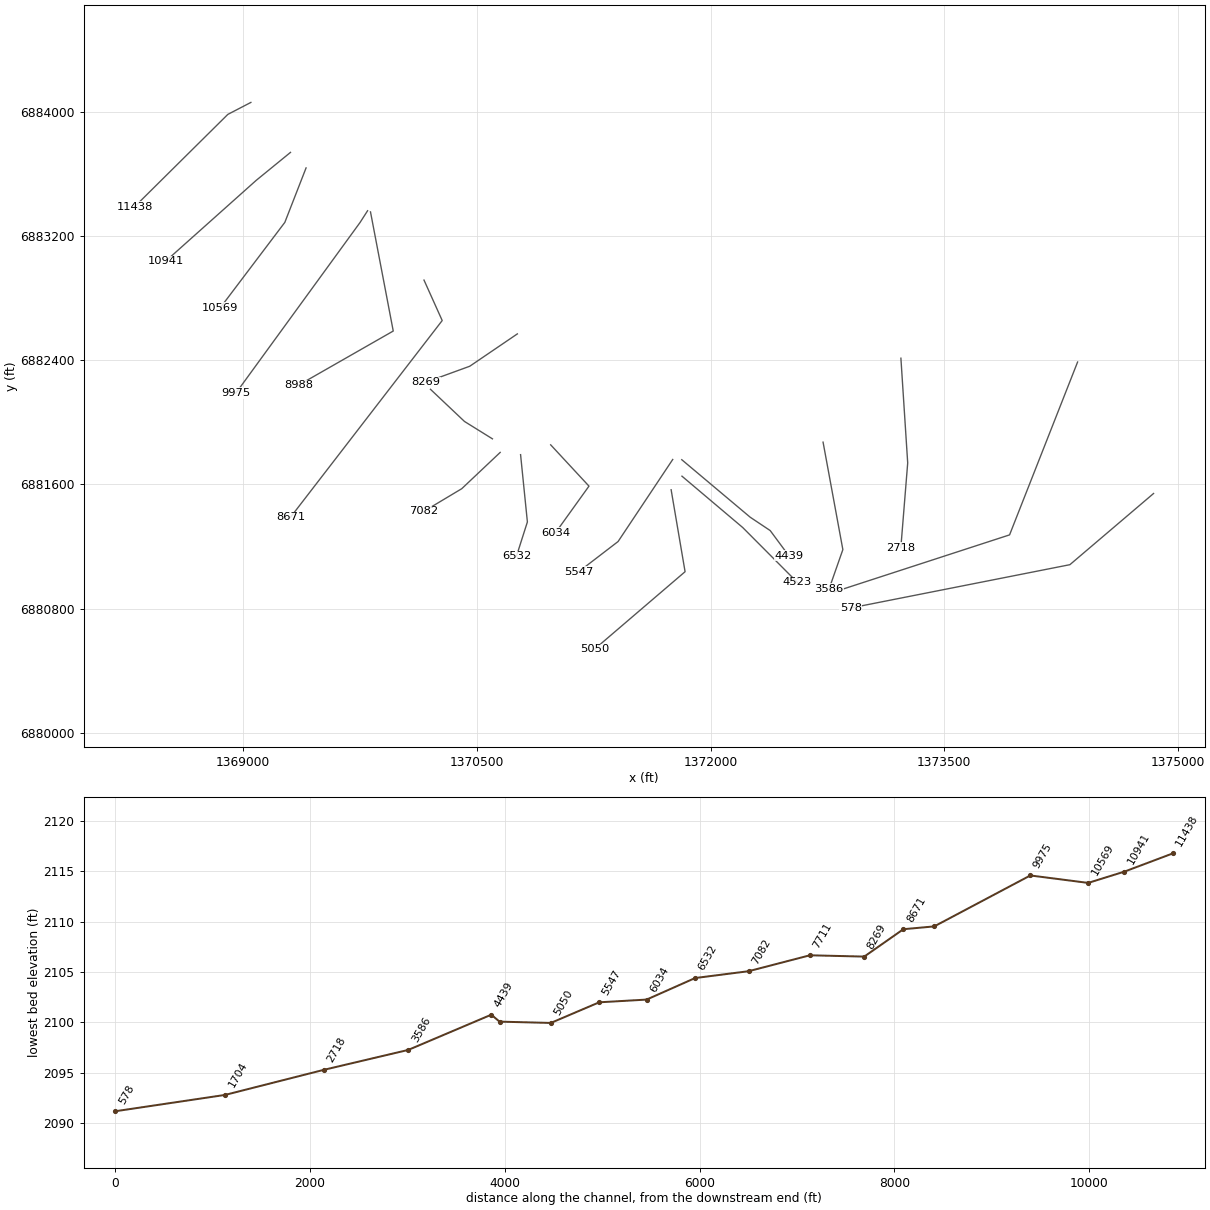
HEC-RAS study Sweetwater Creek Trib 27 T3.prj: Sweetwater Creek Trib 27 T3 Base Level Engineering

--- Sweetwater Creek Trib 27 T3.g01 (geometry) --- (continued)

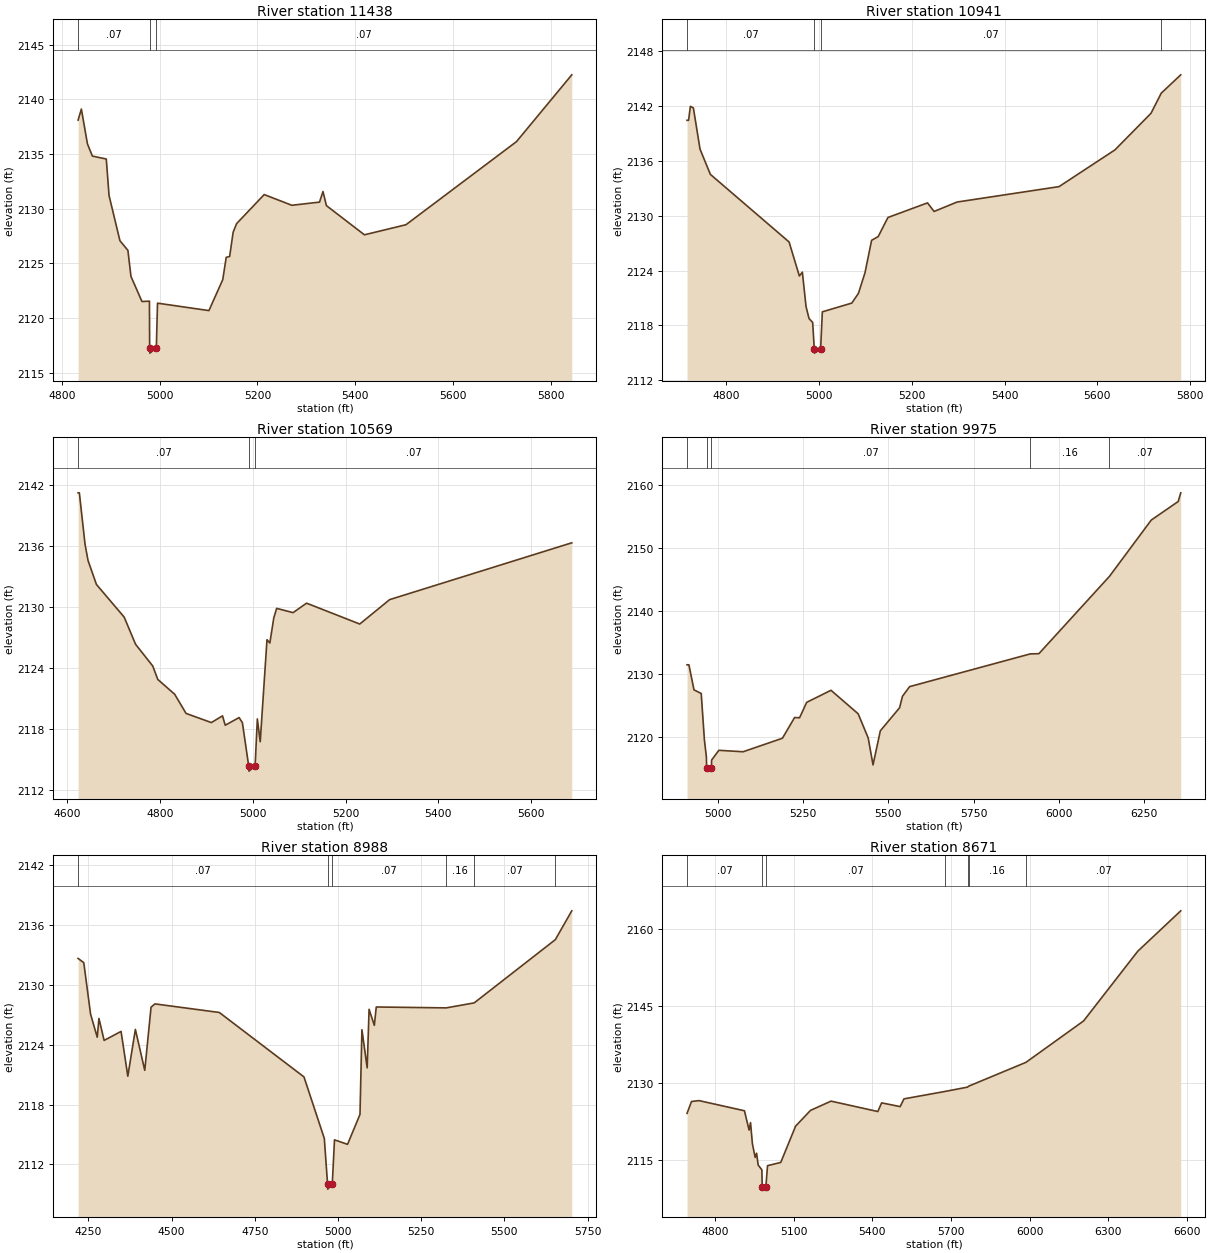
Type RM Length L Ch R = 1,11438,497,497,497
BEGIN DESCRIPTION:
Sweetwater Creek Trib 27 T3 11.0
END DESCRIPTION:
XS GIS Cut Line= 3
      1369050.91      6884059.79      1368902.83      6883982.57
      1368304.97      6883387.97
#Sta/Elev= 30
  4833.0 2138.09  4839.7 2139.10  4852.1 2135.92  4862.2 2134.80  4890.7 2134.53
  4896.3 2131.20  4918.6 2127.06  4934.9 2126.18  4941.2 2123.79  4963.7 2121.50
  4979.0 2121.53  4979.4 2117.28  4979.9 2116.78  4993.1 2117.28  4995.5 2121.35
  5100.7 2120.67  5129.0 2123.50  5136.1 2125.54  5143.1 2125.62  5150.2 2127.83
  5157.3 2128.62  5213.8 2131.28  5270.4 2130.30  5327.0 2130.59  5334.1 2131.56
  5341.1 2130.27  5418.9 2127.60  5503.8 2128.52  5730.0 2136.12  5843.2 2142.23
#Mann=3,-1,0
  4833.0    0.07       0  4979.4    0.07       0  4993.1    0.07       0
Bank Sta=4979.4,4993.1
Exp/Cntr=0.3,0.1

Type RM Length L Ch R = 1,10941,372,372,372
BEGIN DESCRIPTION:
Sweetwater Creek Trib 27 T3 10.0
END DESCRIPTION:
XS GIS Cut Line= 3
      1369305.03      6883738.02      1369085.37      6883558.15
      1368504.97      6883037.97
#Sta/Elev= 30
  4716.1 2140.46  4719.4 2140.46  4723.3 2141.99  4729.8 2141.81  4744.1 2137.30
  4766.4 2134.54  4935.9 2127.14  4958.0 2123.42  4964.5 2123.83  4972.4 2120.08
  4978.8 2118.76  4986.7 2118.33  4990.1 2115.47  4990.6 2114.97  5003.9 2115.47
  5007.5 2119.49  5071.0 2120.45  5085.2 2121.51  5099.4 2123.77  5113.6 2127.32
  5127.8 2127.73  5148.8 2129.82  5234.0 2131.42  5248.2 2130.48  5297.5 2131.51
  5517.3 2133.20  5637.7 2137.22  5715.4 2141.23  5737.4 2143.43  5779.4 2145.44
#Mann=4,-1,0
  4716.1    0.07       0  4990.1    0.07       0  5003.9    0.07       0
  5737.4    0.16       0
Bank Sta=4990.1,5003.9
Exp/Cntr=0.3,0.1

Type RM Length L Ch R = 1,10569,594,594,594
BEGIN DESCRIPTION:
Sweetwater Creek Trib 27 T3 9.0
END DESCRIPTION:
XS GIS Cut Line= 3
      1369405.01      6883638.04      1369268.70      6883287.19
      1368854.98      6882737.98
#Sta/Elev= 30
  4623.6 2141.19  4626.3 2141.19  4638.6 2136.12  4645.1 2134.53  4663.1 2132.19
  4722.9 2128.98  4747.5 2126.31  4784.6 2124.17  4795.3 2122.86  4831.8 2121.40
  4856.3 2119.52  4910.8 2118.62  4934.8 2119.28  4940.7 2118.36  4970.6 2119.11
  4977.7 2118.61  4991.3 2114.35  4991.8 2113.85  5005.1 2114.35  5009.9 2118.98
  5016.1 2116.74  5030.7 2126.76  5036.9 2126.44  5045.3 2128.90  5051.5 2129.84
  5086.9 2129.42  5116.0 2130.35  5230.6 2128.30  5295.1 2130.70  5687.6 2136.28
#Mann=3,-1,0
  4623.6    0.07       0  4991.3    0.07       0  5005.1    0.07       0
Bank Sta=4991.3,5005.1
Exp/Cntr=0.3,0.1

Type RM Length L Ch R = 1,9975,987,987,987
BEGIN DESCRIPTION:
Sweetwater Creek Trib 27 T3 8.0
END DESCRIPTION:
XS GIS Cut Line= 3
      1369799.64      6883362.27      1369751.48      6883286.72
      1368955.02      6882188.03
#Sta/Elev= 30
  4910.4 2131.44  4915.9 2131.44  4930.8 2127.47  4952.0 2126.89  4961.3 2119.55
  4967.2 2116.79  4967.8 2115.09  4968.3 2114.59  4981.7 2115.09  4982.4 2116.34
  5003.6 2117.89  5074.7 2117.66  5189.9 2119.80  5225.5 2123.08  5240.2 2123.05
  5261.0 2125.49  5332.2 2127.40  5411.8 2123.68  5441.2 2119.85  5455.4 2115.58
  5476.8 2120.98  5533.2 2124.63  5541.7 2126.45  5562.6 2127.98  5916.4 2133.17
  5941.4 2133.20  6148.1 2145.45  6270.6 2154.37  6349.7 2157.32  6357.0 2158.69
#Mann=5,-1,0
  4910.4    0.07       0  4967.8    0.07       0  4981.7    0.07       0
  5916.4    0.16       0  6148.1    0.07       0
Bank Sta=4967.8,4981.7
Exp/Cntr=0.3,0.1

Type RM Length L Ch R = 1,8988,317,317,317
BEGIN DESCRIPTION:
Sweetwater Creek Trib 27 T3 7.0
END DESCRIPTION:
XS GIS Cut Line= 3
      1369818.36      6883354.79      1369964.28      6882587.54
      1369355.02      6882238.01
#Sta/Elev= 30
  4219.0 2132.66  4236.1 2132.23  4256.5 2127.07  4276.5 2124.76  4281.6 2126.64
  4297.2 2124.44  4348.1 2125.34  4368.4 2120.85  4391.1 2125.54  4419.3 2121.44
  4438.2 2127.77  4449.9 2128.10  4643.3 2127.24  4897.7 2120.78  4958.8 2114.61
  4968.6 2110.03  4969.1 2109.53  4982.7 2110.03  4989.4 2114.47  5028.6 2114.02
  5066.0 2117.02  5071.8 2125.51  5087.6 2121.69  5093.3 2127.56  5109.1 2125.95
  5114.9 2127.79  5325.1 2127.70  5409.1 2128.20  5652.9 2134.54  5702.4 2137.43
#Mann=6,-1,0
  4219.0    0.07       0  4968.6    0.07       0  4982.7    0.07       0
  5325.1    0.16       0  5409.1    0.07       0  5652.9    0.16       0
Bank Sta=4968.6,4982.7
Exp/Cntr=0.3,0.1

Type RM Length L Ch R = 1,8671,402,402,402
BEGIN DESCRIPTION:
Sweetwater Creek Trib 27 T3 6.0
END DESCRIPTION:
XS GIS Cut Line= 3
      1370161.63      6882915.61      1370278.43      6882655.10
      1369305.03      6881388.04
#Sta/Elev= 30
  4693.1 2124.04  4710.2 2126.36  4738.9 2126.53  4912.1 2124.55  4929.8 2120.78
  4935.3 2122.24  4942.5 2118.10  4953.0 2115.44  4958.5 2116.26  4964.5 2113.95
  4978.6 2113.01  4979.8 2109.75  4980.3 2109.25  4993.9 2109.75  5000.2 2113.83
  5050.6 2114.46  5107.3 2121.55  5164.1 2124.62  5242.4 2126.43  5420.9 2124.40
  5435.4 2126.09  5506.1 2125.36  5520.6 2126.87  5676.2 2128.31  5763.0 2129.16
  5767.5 2129.35  5986.0 2134.00  6205.8 2142.08  6412.5 2155.69  6576.4 2163.58
#Mann=7,-1,0
  4693.1    0.07       0  4979.8    0.07       0  4993.9    0.07       0
  5676.2    0.16       0  5763.0    0.07       0  5767.5    0.16       0
  5986.0    0.07       0
Bank Sta=4979.8,4993.9
Exp/Cntr=0.3,0.1

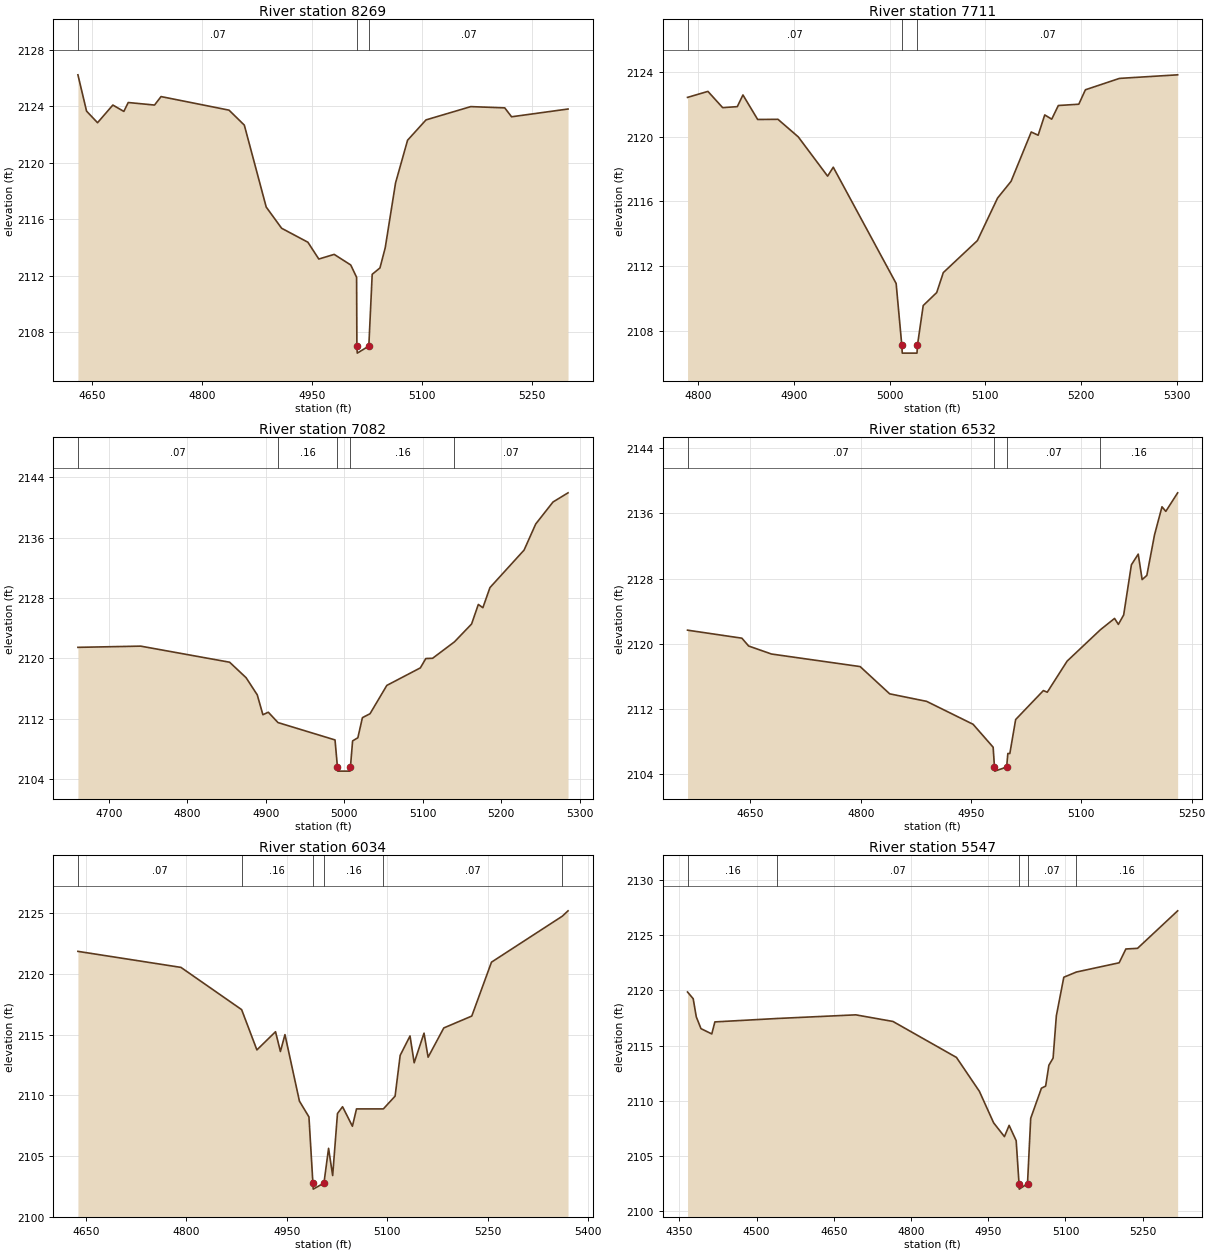
Type RM Length L Ch R = 1,8269,558,558,558
BEGIN DESCRIPTION:
Sweetwater Creek Trib 27 T3 4032
END DESCRIPTION:
XS GIS Cut Line= 3
      1370760.54      6882569.14      1370455.05      6882360.74
      1370173.87      6882257.89
#Sta/Elev= 30
  4630.2 2126.23  4642.0 2123.66  4657.0 2122.84  4677.9 2124.09  4692.9 2123.64
  4698.9 2124.27  4734.8 2124.09  4743.7 2124.69  4836.5 2123.73  4857.4 2122.67
  4887.3 2116.87  4908.3 2115.37  4944.2 2114.38  4959.1 2113.19  4980.1 2113.52
  5002.7 2112.77  5010.7 2111.90  5011.1 2107.03  5011.6 2106.53  5027.4 2107.03
  5032.0 2112.11  5042.6 2112.56  5049.8 2113.99  5063.9 2118.58  5080.3 2121.60
  5105.5 2123.04  5166.6 2123.98  5213.0 2123.89  5222.3 2123.26  5299.4 2123.81
#Mann=3,-1,0
  4630.2    0.07       0  5011.1    0.07       0  5027.4    0.07       0
Bank Sta=5011.1,5027.4
Exp/Cntr=0.3,0.1

Type RM Length L Ch R = 1,7711,629,629,629
BEGIN DESCRIPTION:
Sweetwater Creek Trib 27 T3 4031
END DESCRIPTION:
XS GIS Cut Line= 3
      1370600.67      6881893.29      1370421.49      6882005.10
      1370203.17      6882212.31
#Sta/Elev= 30
  4788.8 2122.41  4810.1 2122.78  4825.5 2121.78  4840.8 2121.84  4846.7 2122.56
  4862.1 2121.05  4883.3 2121.06  4904.5 2119.98  4935.2 2117.56  4941.1 2118.11
  5006.8 2110.95  5012.7 2107.16  5013.2 2106.66  5028.6 2106.66  5029.1 2107.16
  5035.1 2109.59  5049.2 2110.39  5056.1 2111.62  5091.7 2113.59  5112.8 2116.21
  5126.9 2117.24  5148.0 2120.28  5155.2 2120.08  5162.1 2121.33  5169.4 2121.07
  5176.3 2121.91  5197.7 2121.99  5204.6 2122.88  5240.2 2123.58  5301.0 2123.80
#Mann=3,-1,0
  4788.8    0.07       0  5012.7    0.07       0  5029.1    0.07       0
Bank Sta=5012.7,5029.1
Exp/Cntr=0.3,0.1

Type RM Length L Ch R = 1,7082,550,550,550
BEGIN DESCRIPTION:
Sweetwater Creek Trib 27 T3 4030
END DESCRIPTION:
XS GIS Cut Line= 3
      1370650.38      6881805.83      1370403.98      6881572.29
      1370159.67      6881425.53
#Sta/Elev= 30
  4660.5 2121.47  4740.5 2121.63  4853.8 2119.50  4874.8 2117.45  4889.0 2115.18
  4896.2 2112.55  4903.1 2112.88  4915.4 2111.51  4988.1 2109.21  4991.2 2105.58
  4991.7 2105.08  5007.2 2105.08  5007.7 2105.58  5010.5 2109.08  5017.2 2109.50
  5023.0 2112.16  5032.7 2112.68  5054.1 2116.43  5096.8 2118.75  5103.8 2119.99
  5112.4 2120.02  5140.3 2122.20  5162.1 2124.56  5170.7 2127.15  5176.5 2126.72
  5185.5 2129.38  5229.0 2134.35  5243.8 2137.80  5265.9 2140.72  5285.0 2141.93
#Mann=5,-1,0
  4660.5    0.07       0  4915.4    0.16       0  4991.2    0.07       0
  5007.7    0.16       0  5140.3    0.07       0
Bank Sta=4991.2,5007.7
Exp/Cntr=0.3,0.1

Type RM Length L Ch R = 1,6532,498,498,498
BEGIN DESCRIPTION:
Sweetwater Creek Trib 27 T3 5.0
END DESCRIPTION:
XS GIS Cut Line= 3
      1370781.23      6881791.48      1370824.96      6881358.08
      1370755.01      6881138.03
#Sta/Elev= 30
  4564.4 2121.67  4638.3 2120.69  4647.5 2119.73  4678.5 2118.75  4799.1 2117.21
  4839.3 2113.87  4889.5 2112.95  4952.7 2110.14  4980.0 2107.33  4981.8 2104.90
  4982.3 2104.40  4998.3 2104.90  5000.0 2106.56  5002.7 2106.56  5010.6 2110.72
  5048.3 2114.27  5053.6 2114.07  5080.6 2117.88  5125.8 2121.72  5145.1 2123.11
  5150.3 2122.38  5157.5 2123.54  5168.0 2129.68  5177.3 2130.99  5182.6 2127.87
  5189.0 2128.38  5199.5 2133.37  5209.6 2136.79  5214.8 2136.23  5230.9 2138.50
#Mann=4,-1,0
  4564.4    0.07       0  4981.8    0.07       0  4998.3    0.07       0
  5125.8    0.16       0
Bank Sta=4981.8,4998.3
Exp/Cntr=0.3,0.1

Type RM Length L Ch R = 1,6034,487,487,487
BEGIN DESCRIPTION:
Sweetwater Creek Trib 27 T3 4.0
END DESCRIPTION:
XS GIS Cut Line= 3
      1370974.42      6881854.62      1371220.07      6881588.72
      1371005.01      6881288.01
#Sta/Elev= 30
  4638.0 2121.85  4791.8 2120.53  4882.4 2117.05  4905.2 2113.73  4933.0 2115.23
  4940.3 2113.60  4947.1 2114.99  4968.7 2109.51  4982.9 2108.21  4988.8 2102.76
  4989.3 2102.26  5005.3 2102.76  5012.2 2105.62  5018.3 2103.38  5025.5 2108.49
  5033.1 2109.05  5047.8 2107.44  5053.9 2108.87  5094.0 2108.87  5111.5 2109.92
  5119.1 2113.28  5133.8 2114.88  5140.0 2112.67  5154.7 2115.11  5160.8 2113.13
  5184.2 2115.54  5226.0 2116.52  5255.4 2120.96  5361.2 2124.75  5369.7 2125.19
#Mann=6,-1,0
  4638.0    0.07       0  4882.4    0.16       0  4988.8    0.07       0
  5005.3    0.16       0  5094.0    0.07       0  5361.2    0.16       0
Bank Sta=4988.8,5005.3
Exp/Cntr=0.3,0.1

Type RM Length L Ch R = 1,5547,497,497,497
BEGIN DESCRIPTION:
Sweetwater Creek Trib 27 T3 3.0
END DESCRIPTION:
XS GIS Cut Line= 3
      1371757.38      6881760.27      1371406.89      6881231.96
      1371155.01      6881038.01
#Sta/Elev= 30
  4366.0 2119.86  4377.0 2119.25  4383.0 2117.61  4392.1 2116.54  4413.1 2116.06
  4419.1 2117.15  4540.2 2117.46  4692.8 2117.79  4765.0 2117.19  4888.3 2113.93
  4932.8 2110.86  4960.5 2108.00  4981.5 2106.75  4990.6 2107.77  5004.3 2106.38
  5009.8 2102.49  5010.3 2101.99  5026.3 2102.49  5032.5 2108.41  5053.3 2111.14
  5061.5 2111.33  5067.8 2113.22  5076.0 2113.87  5082.3 2117.70  5096.8 2121.20
  5121.1 2121.67  5204.3 2122.51  5217.3 2123.76  5240.0 2123.82  5317.9 2127.22
#Mann=5,-1,0
  4366.0    0.16       0  4540.2    0.07       0  5009.8    0.07       0
  5026.3    0.07       0  5121.1    0.16       0
Bank Sta=5009.8,5026.3
Exp/Cntr=0.3,0.1

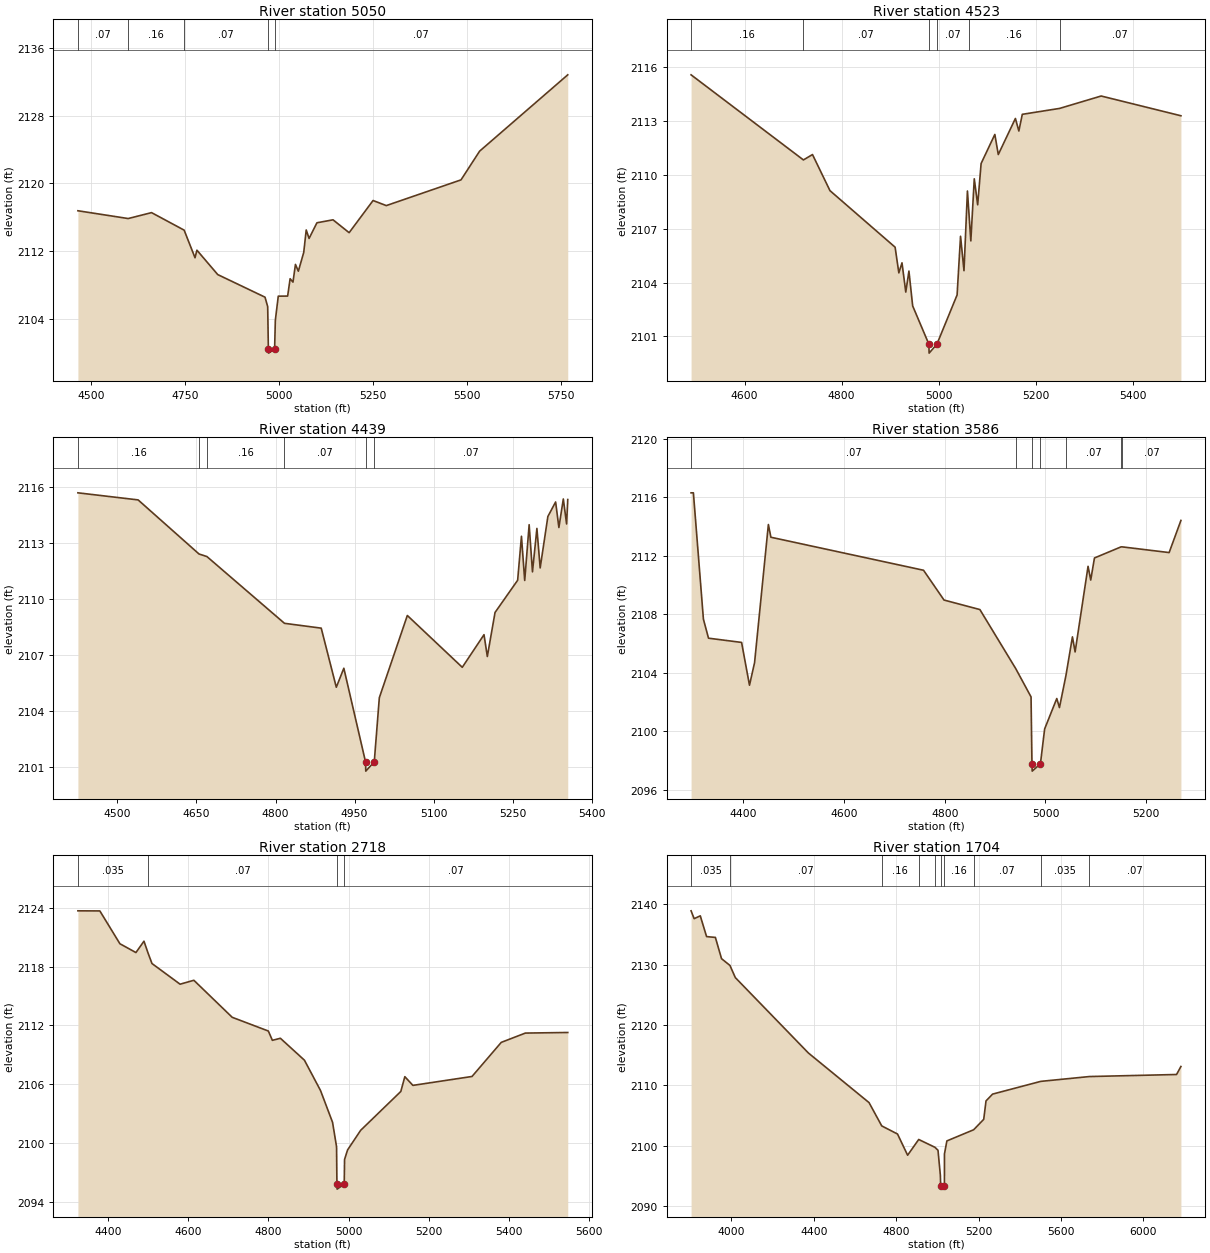
Type RM Length L Ch R = 1,5050,527,527,527
BEGIN DESCRIPTION:
Sweetwater Creek Trib 27 T3 2.0
END DESCRIPTION:
XS GIS Cut Line= 3
      1371747.18      6881565.37      1371836.66      6881037.60
      1371254.97      6880537.97
#Sta/Elev= 30
  4464.7 2116.76  4598.4 2115.84  4660.4 2116.54  4747.1 2114.47  4776.0 2111.21
  4781.1 2112.10  4836.4 2109.22  4962.1 2106.55  4969.2 2105.43  4971.0 2100.44
  4971.5 2099.94  4987.6 2100.44  4989.5 2103.81  4997.3 2106.67  5022.2 2106.68
  5028.8 2108.73  5036.4 2108.33  5043.0 2110.42  5050.7 2109.62  5065.0 2111.84
  5071.6 2114.49  5079.2 2113.49  5100.1 2115.34  5142.9 2115.69  5185.7 2114.17
  5249.3 2117.97  5284.5 2117.37  5483.1 2120.41  5532.5 2123.80  5766.8 2132.82
#Mann=5,-1,0
  4464.7    0.07       0  4598.4    0.16       0  4747.1    0.07       0
  4971.0    0.07       0  4987.6    0.07       0
Bank Sta=4971,4987.6
Exp/Cntr=0.3,0.1

Type RM Length L Ch R = 1,4523,84,84,84
BEGIN DESCRIPTION:
Sweetwater Creek Trib 27 T3 4026
END DESCRIPTION:
XS GIS Cut Line= 3
      1371816.64      6881652.80      1372205.87      6881322.64
      1372557.65      6880968.17
#Sta/Elev= 30
  4489.6 2115.57  4721.2 2110.83  4739.9 2111.13  4775.9 2109.12  4910.2 2105.97
  4917.9 2104.54  4924.4 2105.10  4932.2 2103.47  4938.7 2104.64  4946.4 2102.70
  4979.8 2100.57  4980.3 2100.07  4996.4 2100.57  5038.0 2103.31  5045.1 2106.58
  5052.2 2104.66  5059.3 2109.10  5061.5 2108.23  5066.3 2106.32  5073.4 2109.78
  5080.4 2108.33  5087.5 2110.63  5115.8 2112.25  5122.9 2111.13  5158.2 2113.14
  5165.3 2112.44  5172.4 2113.37  5249.4 2113.70  5335.0 2114.39  5499.4 2113.29
#Mann=6,-1,0
  4489.6    0.16       0  4721.2    0.07       0  4979.8    0.07       0
  4996.4    0.07       0  5061.5    0.16       0  5249.4    0.07       0
Bank Sta=4979.8,4996.4
Exp/Cntr=0.3,0.1

Type RM Length L Ch R = 1,4439,853,853,853
BEGIN DESCRIPTION:
Sweetwater Creek Trib 27 T3 4024
END DESCRIPTION:
XS GIS Cut Line= 4
      1371815.41      6881758.89      1372254.69      6881388.34
      1372382.77      6881302.54      1372501.57      6881141.61
#Sta/Elev= 30
  4425.3 2115.69  4539.5 2115.31  4654.9 2112.41  4670.0 2112.27  4817.0 2108.69
  4886.7 2108.43  4915.3 2105.26  4929.6 2106.28  4970.7 2101.26  4971.2 2100.76
  4987.3 2101.26  4996.9 2104.70  5050.0 2109.11  5154.2 2106.33  5195.4 2108.08
  5201.7 2106.91  5216.3 2109.27  5259.2 2111.00  5266.4 2113.36  5272.6 2110.99
  5281.0 2113.98  5287.3 2111.45  5295.7 2113.78  5301.9 2111.66  5316.5 2114.42
  5331.2 2115.20  5337.4 2113.83  5345.8 2115.36  5352.0 2114.02  5354.2 2115.33
#Mann=6,-1,0
  4425.3    0.16       0  4654.9    0.07       0  4670.0    0.16       0
  4817.0    0.07       0  4970.7    0.07       0  4987.3    0.07       0
Bank Sta=4970.7,4987.3
Exp/Cntr=0.3,0.1

Type RM Length L Ch R = 1,3586,868,868,868
BEGIN DESCRIPTION:
Sweetwater Creek Trib 27 T3 4025
END DESCRIPTION:
XS GIS Cut Line= 3
      1372721.96      6881872.05      1372848.93      6881179.90
      1372760.30      6880925.92
#Sta/Elev= 30
  4296.3 2116.31  4300.9 2116.31  4320.8 2107.66  4330.9 2106.36  4396.6 2106.07
  4412.3 2103.14  4422.4 2104.69  4449.8 2114.14  4454.8 2113.27  4757.9 2111.01
  4798.6 2108.97  4869.8 2108.32  4941.1 2104.27  4971.4 2102.34  4973.2 2097.76
  4973.7 2097.26  4990.0 2097.76  4998.4 2100.15  5022.5 2102.23  5027.8 2101.61
  5040.7 2103.81  5053.6 2106.45  5058.9 2105.42  5084.6 2111.28  5089.9 2110.34
  5097.3 2111.85  5150.1 2112.61  5152.6 2112.61  5245.6 2112.22  5269.0 2114.42
#Mann=7,-1,0
  4296.3    0.07       0  4941.1    0.16       0  4973.2    0.07       0
  4990.0    0.16       0  5040.7    0.07       0  5150.1    0.16       0
  5152.6    0.07       0
Bank Sta=4973.2,4990
Exp/Cntr=0.3,0.1

Type RM Length L Ch R = 1,2718,1014,1014,1014
BEGIN DESCRIPTION:
Sweetwater Creek Trib 27 T3 4023
END DESCRIPTION:
XS GIS Cut Line= 3
      1373221.36      6882412.64      1373264.98      6881738.05
      1373220.95      6881192.43
#Sta/Elev= 30
  4324.0 2123.69  4378.8 2123.68  4428.9 2120.33  4468.9 2119.43  4489.0 2120.59
  4499.1 2119.39  4509.0 2118.31  4579.2 2116.20  4613.6 2116.60  4709.4 2112.82
  4799.6 2111.42  4809.7 2110.47  4829.7 2110.68  4889.8 2108.44  4929.9 2105.35
  4960.0 2102.10  4970.0 2099.60  4970.9 2095.78  4971.4 2095.28  4989.1 2095.78
  4990.0 2098.31  4997.5 2099.28  5030.1 2101.28  5130.5 2105.25  5140.5 2106.76
  5160.6 2105.87  5308.3 2106.78  5381.3 2110.26  5441.5 2111.21  5547.4 2111.27
#Mann=4,-1,0
  4324.0   0.035       0  4499.1    0.07       0  4970.9    0.07       0
  4989.1    0.07       0
Bank Sta=4970.9,4989.1
Exp/Cntr=0.3,0.1

Type RM Length L Ch R = 1,1704,1126,1126,1126
BEGIN DESCRIPTION:
Sweetwater Creek Trib 27 T3 1.0
END DESCRIPTION:
XS GIS Cut Line= 3
      1374354.99      6882387.97      1373918.56      6881274.76
      1372795.13      6880907.93
#Sta/Elev= 30
  3804.3 2138.92  3819.2 2137.62  3849.0 2138.09  3879.5 2134.65  3922.3 2134.51
  3952.1 2130.99  3992.9 2129.87  4019.1 2127.85  4373.5 2115.36  4668.1 2107.13
  4729.7 2103.27  4806.4 2101.92  4855.3 2098.41  4909.1 2101.02  4987.6 2099.73
  5002.8 2099.23  5014.3 2095.05  5015.6 2093.29  5016.1 2092.79  5033.9 2093.29
  5034.0 2098.59  5045.8 2100.78  5175.8 2102.63  5224.7 2104.36  5235.8 2107.41
  5267.7 2108.54  5501.4 2110.65  5737.4 2111.45  6160.6 2111.79  6181.8 2113.12
#Mann=10,-1,0
  3804.3   0.035       0  3992.9    0.07       0  4729.7    0.16       0
  4909.1    0.07       0  4987.6    0.16       0  5015.6    0.07       0
  5033.9    0.16       0  5175.8    0.07       0  5501.4   0.035       0
  5737.4    0.07       0
Bank Sta=5015.6,5033.9
Exp/Cntr=0.3,0.1

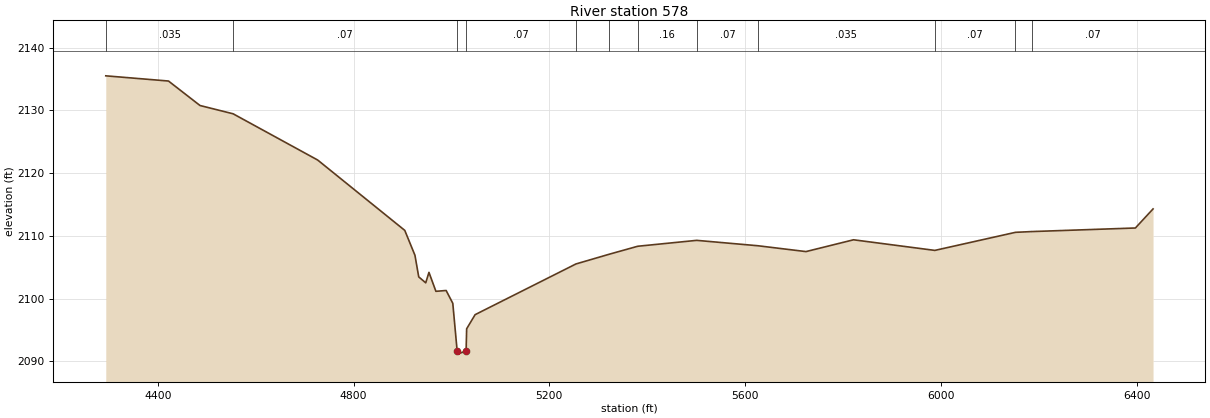
Type RM Length L Ch R = 1,578,0,0,0
BEGIN DESCRIPTION:
Sweetwater Creek Trib 27 T3 1889
END DESCRIPTION:
XS GIS Cut Line= 3
      1374842.43      6881541.35      1374305.48      6881082.80
      1372899.55      6880804.06
#Sta/Elev= 30
  4293.9 2135.52  4422.0 2134.69  4486.4 2130.79  4554.0 2129.47  4726.8 2122.10
  4904.7 2110.89  4925.5 2106.92  4933.2 2103.48  4947.5 2102.53  4954.1 2104.20
  4968.3 2101.18  4989.2 2101.31  5002.8 2099.27  5011.7 2091.67  5012.2 2091.17
  5030.0 2091.67  5031.1 2095.21  5048.4 2097.46  5254.4 2105.54  5322.4 2107.09
  5380.6 2108.36  5501.1 2109.30  5626.2 2108.44  5724.3 2107.51  5821.4 2109.39
  5987.5 2107.70  6152.3 2110.58  6185.6 2110.70  6397.2 2111.27  6433.3 2114.31
#Mann=12,-1,0
  4293.9   0.035       0  4554.0    0.07       0  5011.7    0.07       0
  5030.0    0.07       0  5254.4    0.16       0  5322.4    0.07       0
  5380.6    0.16       0  5501.1    0.07       0  5626.2   0.035       0
  5987.5    0.07       0  6152.3   0.035       0  6185.6    0.07       0
Bank Sta=5011.7,5030
Exp/Cntr=0.3,0.1

Chan Stop Cuts=-1