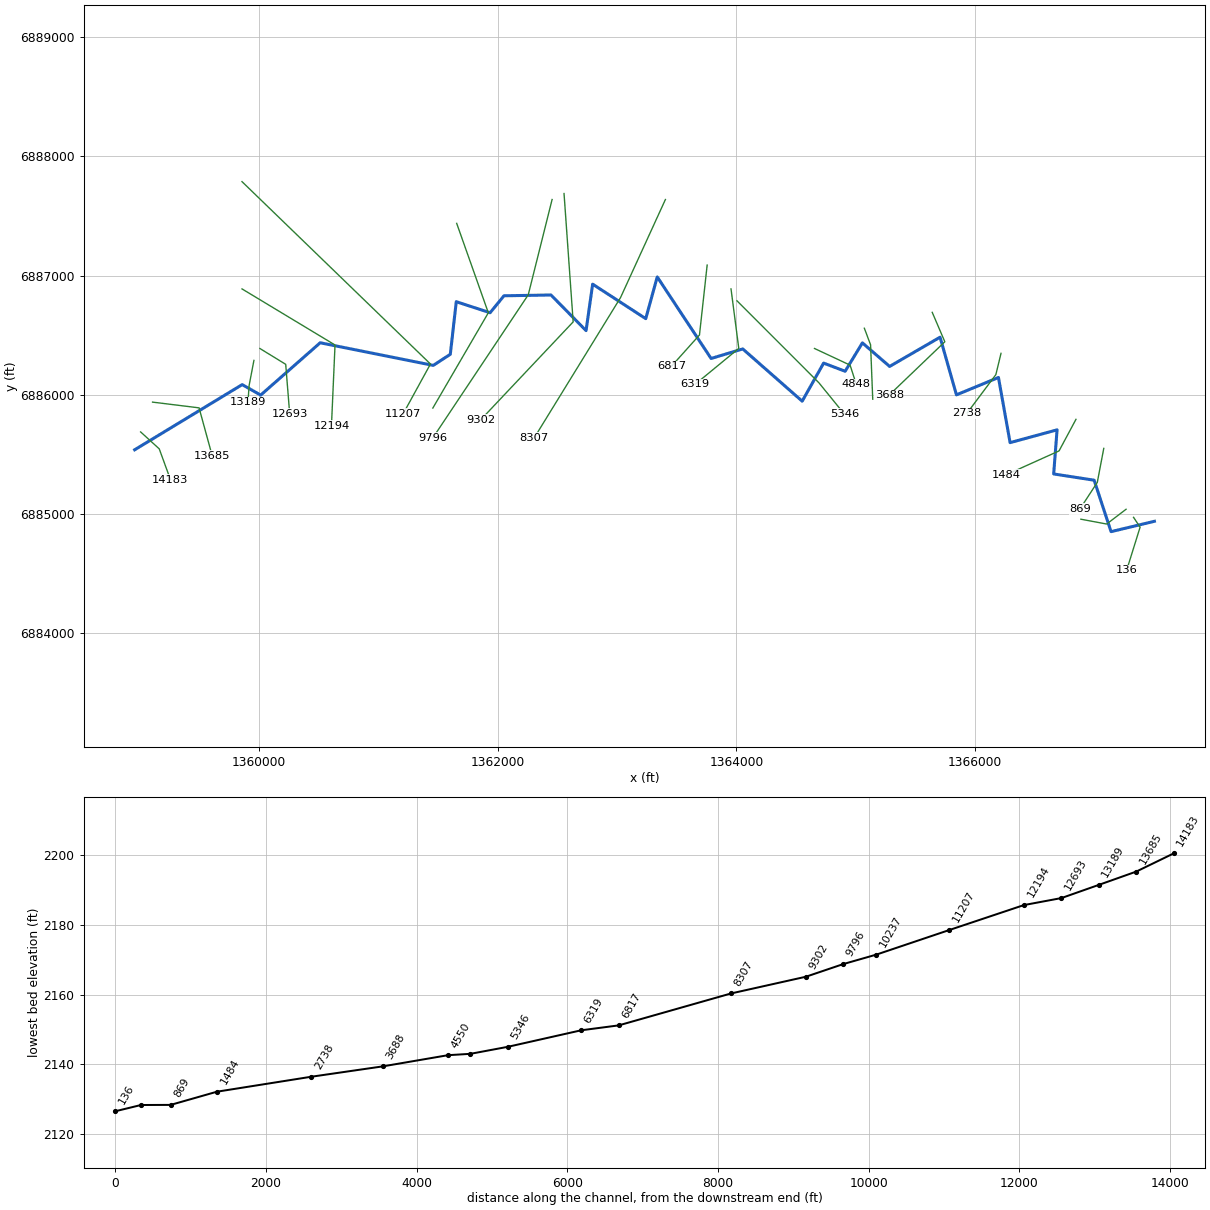
--- Sweetwater Creek Trib 27 T3_1.prj (project) ---

Proj Title=Sweetwater Creek Trib 27 T3_1 Base Level Engineering
Current Plan=p01
Default Exp/Contr=0.3,0.1
English Units
Geom File=g01
Flow File=f01
Plan File=p01
Y Axis Title=Elevation
X Axis Title(PF)=Main Channel Distance
X Axis Title(XS)=Station
BEGIN DESCRIPTION:
Sweetwater Creek Trib 27 T3_1
END DESCRIPTION:
DSS Export Rating Curves= 0
DSS Export Rating Curve Sorted= 0
DSS Export Volume Flow Curves= 0
DXF OffsetX= 0
DXF OffsetY= 0
DXF ScaleX= 1
DXF ScaleY= 10

--- Sweetwater Creek Trib 27 T3_1.p01 (plan) ---

Plan Title=Multiple Run
Short Identifier=Multiple
Geom File=g01
Flow File=f01
Subcritical Flow
K Sum by GR= 0
Std Step Tol= 0.01
Critical Tol= 0.01
Num of Std Step Trials= 20
Max Error Tol= 0.3
Flow Tol Ratio= 0.001
Split Flow NTrial= 30
Split Flow Tol= 0.02
Split Flow Ratio= 0.02
Log Output Level= 0
Friction Slope Method= 1
Unsteady Friction Slope Method= 2
Unsteady Bridges Friction Slope Method= 1
Parabolic Critical Depth
Global Vel Dist=  1 , 1 , 1
Global Log Level= 0
CheckData=True
Encroach Param= -1, 0, 0, 0
BEGIN DESCRIPTION:
Multiple Run
END DESCRIPTION:

--- Sweetwater Creek Trib 27 T3_1.f01 (steady flow) ---

Flow Title=Multiple
Number of Profiles=7
Profile Names=10-year,25-year,50-year,1pct_min,100-year,1pct_plu,500-year
River Rch & RM= Sweetwater Creek,Reach-1,14183
     317     459     580     365     729    1455    1166
River Rch & RM= Sweetwater Creek,Reach-1,13189
     405     589     748     472     942    1880    1514
River Rch & RM= Sweetwater Creek,Reach-1,5346
     463     674     855     539    1075    2145    1721
Boundary for River Rch & Prof#=Sweetwater Creek,Reach-1,1
Up Type=0
Dn Type=3
Dn Slope=0.005
Boundary for River Rch & Prof#=Sweetwater Creek,Reach-1,2
Up Type=0
Dn Type=3
Dn Slope=0.005
Boundary for River Rch & Prof#=Sweetwater Creek,Reach-1,3
Up Type=0
Dn Type=3
Dn Slope=0.005
Boundary for River Rch & Prof#=Sweetwater Creek,Reach-1,4
Up Type=0
Dn Type=3
Dn Slope=0.005
Boundary for River Rch & Prof#=Sweetwater Creek,Reach-1,5
Up Type=0
Dn Type=3
Dn Slope=0.005
Boundary for River Rch & Prof#=Sweetwater Creek,Reach-1,6
Up Type=0
Dn Type=3
Dn Slope=0.005
Boundary for River Rch & Prof#=Sweetwater Creek,Reach-1,7
Up Type=0
Dn Type=3
Dn Slope=0.005

--- Sweetwater Creek Trib 27 T3_1.g01 (geometry) ---

Geom Title=Existing Conditions

River Reach=Sweetwater Creek,Reach-1
Reach XY= 30
      1358955.00      6885538.00      1359856.65      6886084.90
      1360011.69      6885996.95      1360510.72      6886436.05
      1361458.31      6886246.02      1361601.55      6886339.25
      1361651.38      6886780.52      1361935.12      6886687.91
      1362051.42      6886830.11      1362445.42      6886836.80
      1362739.76      6886537.84      1362794.89      6886927.70
      1363240.06      6886638.23      1363336.52      6886988.40
      1363787.95      6886304.04      1364053.44      6886384.26
      1364551.77      6885945.84      1364731.47      6886265.32
      1364911.95      6886196.84      1365056.43      6886434.99
      1365284.87      6886237.45      1365707.78      6886482.64
      1365845.11      6885998.89      1366197.31      6886144.57
      1366294.94      6885598.03      1366688.73      6885705.32
      1366660.28      6885335.29      1366999.56      6885282.82
      1367141.26      6884851.19      1367505.00      6884938.00

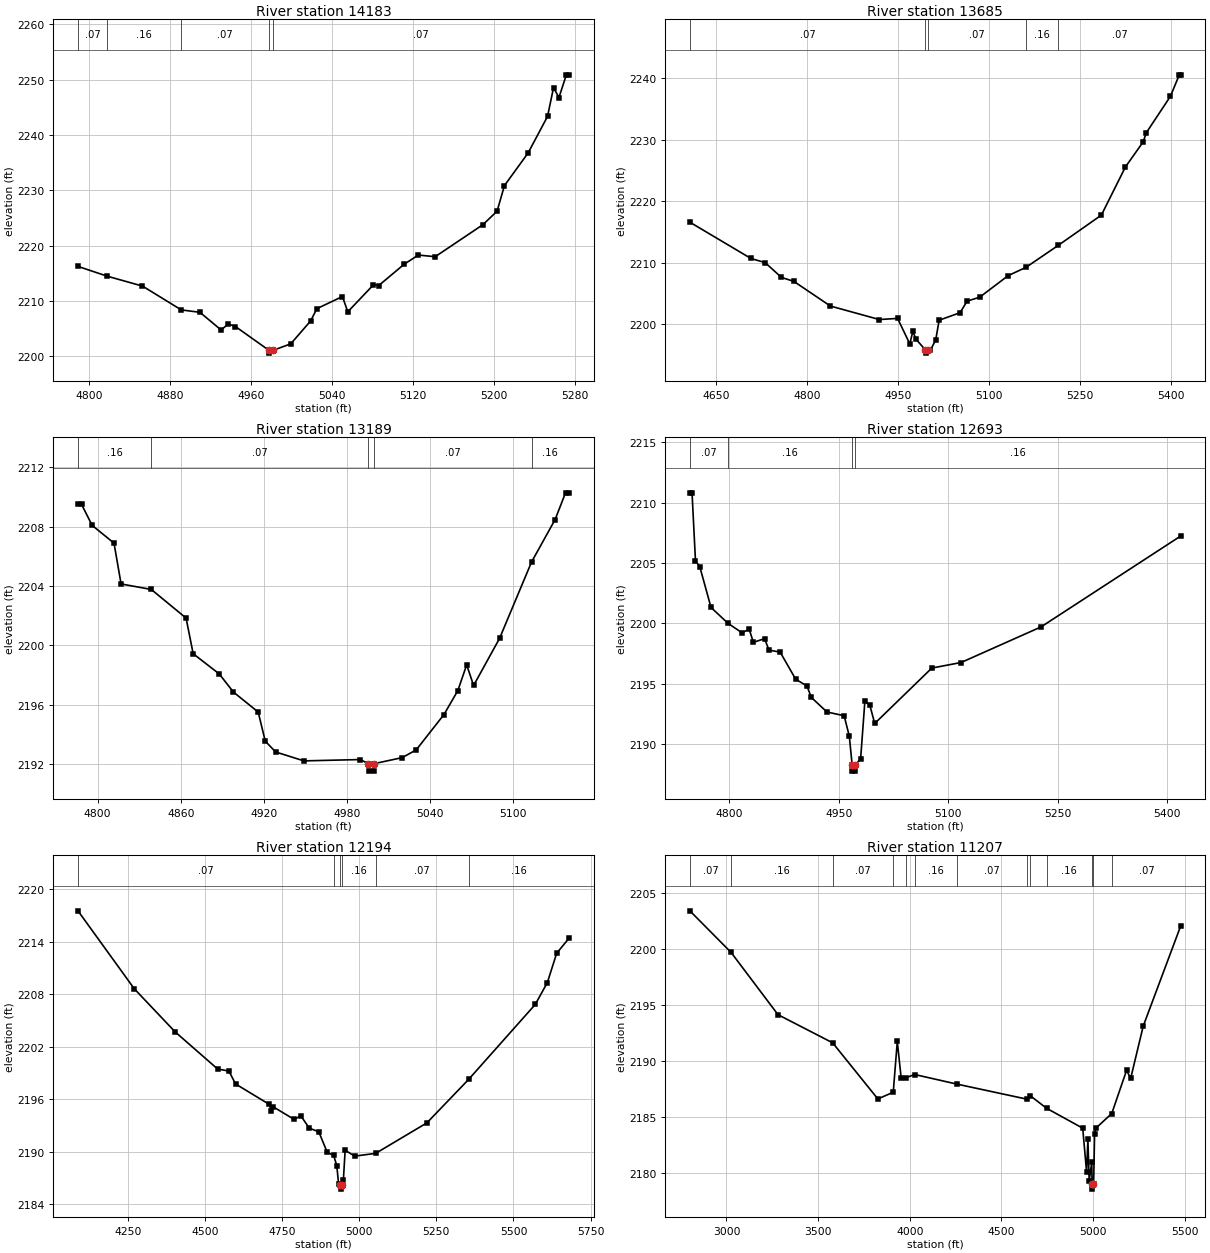
Type RM Length L Ch R = 1,14183,498,498,498
BEGIN DESCRIPTION:
Sweetwater Creek Trib 27 T3_1 15.0
END DESCRIPTION:
XS GIS Cut Line= 3
      1359005.02      6885687.98      1359161.19      6885545.81
      1359254.99      6885288.04
#Sta/Elev= 30
  4788.8 2216.25  4817.7 2214.48  4852.6 2212.69  4891.0 2208.38  4909.4 2207.95
  4930.3 2204.76  4937.5 2205.84  4944.5 2205.38  4977.7 2201.07  4977.9 2200.57
  4981.7 2201.07  4999.2 2202.25  5018.9 2206.40  5025.0 2208.61  5050.3 2210.80
  5055.6 2208.04  5080.9 2212.91  5086.2 2212.79  5111.4 2216.65  5125.4 2218.30
  5142.0 2218.00  5189.2 2223.79  5203.2 2226.23  5210.5 2230.86  5233.8 2236.73
  5253.1 2243.36  5259.0 2248.55  5264.4 2246.78  5271.7 2250.88  5274.3 2250.88
#Mann=5,-1,0
  4788.8    0.07       0  4817.7    0.16       0  4891.0    0.07       0
  4977.7    0.07       0  4981.7    0.07       0
Bank Sta=4977.7,4981.7
Exp/Cntr=0.3,0.1

Type RM Length L Ch R = 1,13685,496,496,496
BEGIN DESCRIPTION:
Sweetwater Creek Trib 27 T3_1 14.0
END DESCRIPTION:
XS GIS Cut Line= 3
      1359104.99      6885938.00      1359495.13      6885889.88
      1359604.99      6885488.02
#Sta/Elev= 30
  4606.9 2216.62  4707.7 2210.72  4731.1 2210.05  4758.0 2207.64  4778.2 2207.01
  4838.7 2202.99  4919.3 2200.80  4949.5 2200.98  4969.6 2196.84  4974.6 2198.87
  4979.7 2197.63  4995.4 2195.84  4995.7 2195.34  4999.4 2195.84  5003.6 2195.84
  5012.3 2197.47  5018.0 2200.69  5052.5 2201.91  5064.1 2203.79  5084.9 2204.43
  5131.9 2207.94  5161.2 2209.28  5214.2 2212.84  5285.5 2217.77  5325.2 2225.60
  5354.4 2229.67  5359.7 2231.17  5399.4 2237.08  5414.0 2240.57  5416.6 2240.57
#Mann=5,-1,0
  4606.9    0.07       0  4995.4    0.07       0  4999.4    0.07       0
  5161.2    0.16       0  5214.2    0.07       0
Bank Sta=4995.4,4999.4
Exp/Cntr=0.3,0.1

Type RM Length L Ch R = 1,13189,496,496,496
BEGIN DESCRIPTION:
Sweetwater Creek Trib 27 T3_1 13.0
END DESCRIPTION:
XS GIS Cut Line= 3
      1359955.01      6886288.05      1359914.68      6886077.78
      1359905.00      6885938.02
#Sta/Elev= 30
  4785.9 2209.50  4788.5 2209.50  4796.1 2208.09  4811.9 2206.89  4817.0 2204.14
  4838.8 2203.77  4863.9 2201.84  4869.0 2199.44  4887.8 2198.08  4898.0 2196.86
  4915.9 2195.51  4921.0 2193.55  4928.5 2192.82  4948.9 2192.22  4989.6 2192.31
  4995.3 2192.03  4995.5 2191.53  4999.1 2191.53  4999.4 2192.03  5019.8 2192.44
  5029.9 2192.96  5049.9 2195.34  5059.9 2196.95  5066.3 2198.69  5071.3 2197.30
  5090.0 2200.47  5113.1 2205.62  5130.1 2208.48  5137.6 2210.28  5140.1 2210.28
#Mann=5,-1,0
  4785.9    0.16       0  4838.8    0.07       0  4995.3    0.07       0
  4999.4    0.07       0  5113.1    0.16       0
Bank Sta=4995.3,4999.4
Exp/Cntr=0.3,0.1

Type RM Length L Ch R = 1,12693,499,499,499
BEGIN DESCRIPTION:
Sweetwater Creek Trib 27 T3_1 12.0
END DESCRIPTION:
XS GIS Cut Line= 3
      1360004.98      6886388.01      1360221.51      6886255.03
      1360255.00      6885837.97
#Sta/Elev= 30
  4745.9 2210.81  4748.9 2210.81  4753.6 2205.18  4759.5 2204.69  4774.9 2201.31
  4798.3 2199.99  4817.5 2199.21  4827.1 2199.52  4832.9 2198.42  4848.3 2198.73
  4854.2 2197.78  4869.6 2197.61  4890.9 2195.36  4906.3 2194.81  4912.2 2193.86
  4933.7 2192.65  4957.2 2192.34  4964.3 2190.64  4968.2 2188.25  4968.4 2187.75
  4972.0 2187.75  4972.3 2188.25  4979.8 2188.77  4985.6 2193.54  4992.4 2193.21
  4999.1 2191.70  5077.3 2196.29  5117.4 2196.75  5226.9 2199.70  5418.4 2207.24
#Mann=4,-1,0
  4745.9    0.07       0  4798.3    0.16       0  4968.2    0.07       0
  4972.3    0.16       0
Bank Sta=4968.2,4972.3
Exp/Cntr=0.3,0.1

Type RM Length L Ch R = 1,12194,987,987,987
BEGIN DESCRIPTION:
Sweetwater Creek Trib 27 T3_1 11.0
END DESCRIPTION:
XS GIS Cut Line= 3
      1359854.97      6886888.02      1360634.93      6886417.29
      1360605.00      6885738.05
#Sta/Elev= 30
  4089.0 2217.53  4271.5 2208.62  4403.5 2203.71  4541.3 2199.46  4578.1 2199.22
  4599.5 2197.75  4708.1 2195.43  4716.0 2194.61  4721.8 2195.13  4789.7 2193.69
  4811.1 2194.11  4838.3 2192.70  4869.3 2192.28  4896.5 2189.94  4917.4 2189.58
  4927.5 2188.42  4933.4 2186.35  4939.6 2186.23  4939.9 2185.73  4943.7 2186.23
  4948.9 2186.77  4954.7 2190.17  4985.8 2189.50  5053.7 2189.82  5219.5 2193.30
  5354.6 2198.26  5570.6 2206.83  5609.9 2209.34  5639.9 2212.67  5679.9 2214.40
#Mann=6,-1,0
  4089.0    0.07       0  4917.4    0.16       0  4939.6    0.07       0
  4943.7    0.16       0  5053.7    0.07       0  5354.6    0.16       0
Bank Sta=4939.6,4943.7
Exp/Cntr=0.3,0.1

Type RM Length L Ch R = 1,11207,970,970,970
BEGIN DESCRIPTION:
Sweetwater Creek Trib 27 T3_1 10.0
END DESCRIPTION:
XS GIS Cut Line= 3
      1359855.01      6887787.99      1361435.13      6886257.67
      1361205.01      6885838.02
#Sta/Elev= 30
  2800.3 2203.43  3025.1 2199.72  3281.2 2194.16  3579.1 2191.65  3825.8 2186.64
  3909.8 2187.24  3931.8 2191.77  3953.1 2188.48  3981.7 2188.55  4026.6 2188.82
  4255.3 2187.97  4638.9 2186.62  4657.6 2186.92  4745.8 2185.81  4943.2 2184.03
  4964.3 2180.13  4971.5 2183.02  4978.4 2179.32  4992.6 2180.98  4994.3 2179.09
  4994.6 2178.59  4998.5 2179.09  5002.7 2179.09  5008.0 2183.54  5013.7 2184.01
  5101.7 2185.34  5182.4 2189.19  5204.9 2188.48  5273.3 2193.14  5478.6 2202.12
#Mann=13,-1,0
  2800.3    0.07       0  3025.1    0.16       0  3579.1    0.07       0
  3909.8    0.16       0  3981.7    0.07       0  4026.6    0.16       0
  4255.3    0.07       0  4638.9    0.16       0  4657.6    0.07       0
  4745.8    0.16       0  4994.3    0.07       0  4998.5    0.16       0
  5101.7    0.07       0
Bank Sta=4994.3,4998.5
Exp/Cntr=0.3,0.1

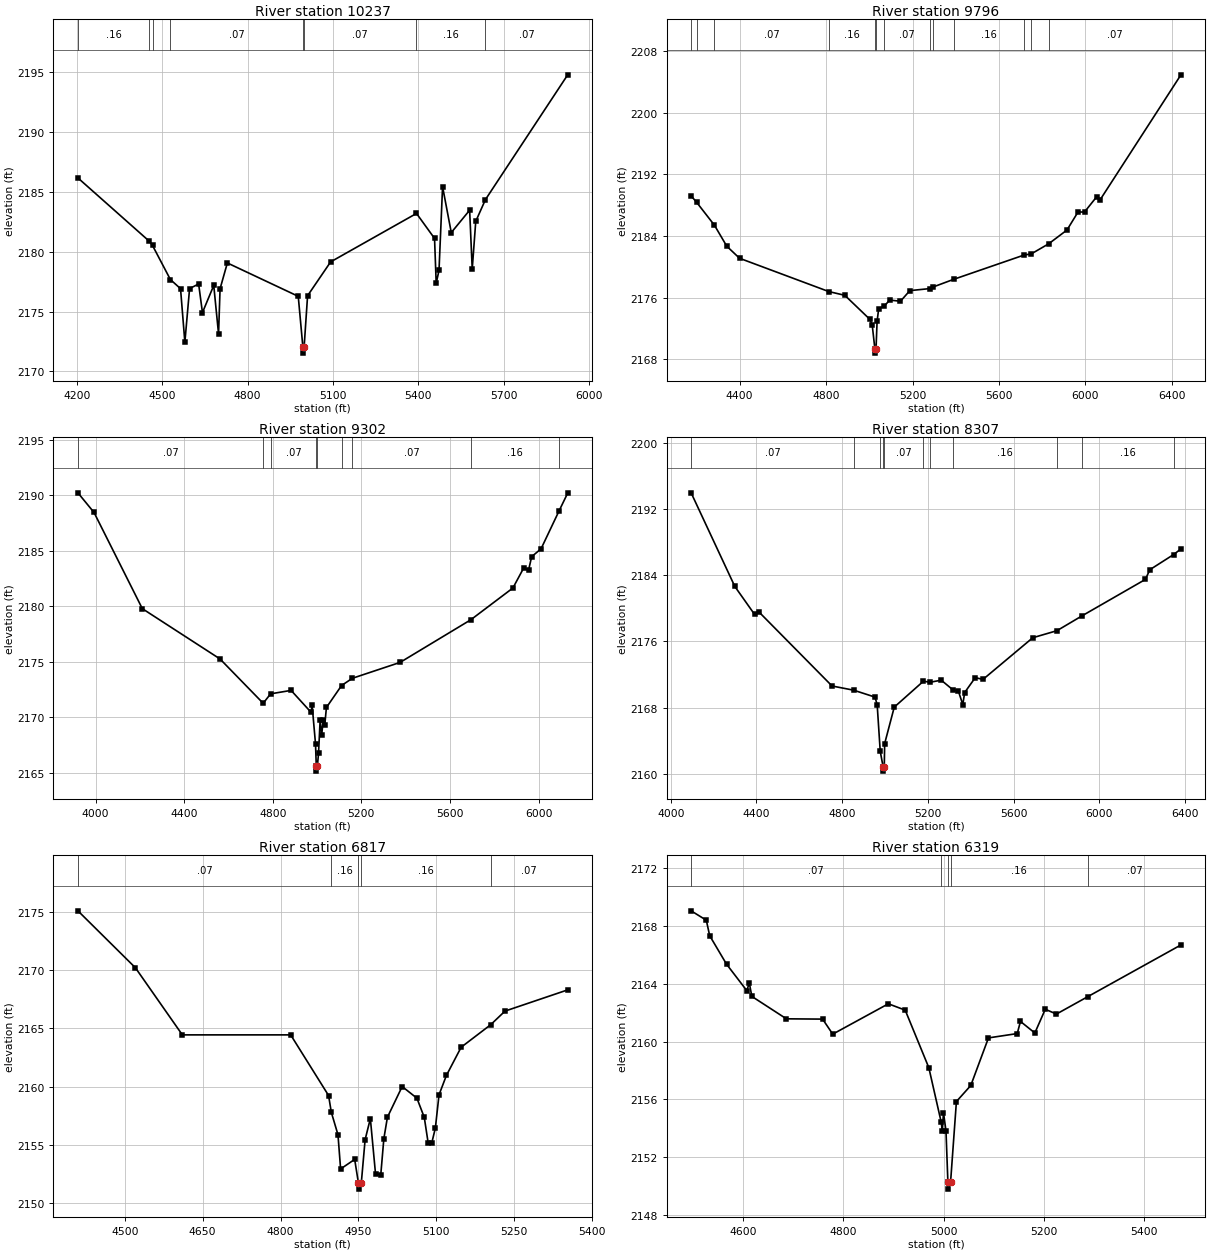
Type RM Length L Ch R = 1,10237,441,441,441
BEGIN DESCRIPTION:
Sweetwater Creek Trib 27 T3_1 9.0
END DESCRIPTION:
XS GIS Cut Line= 3
      1361655.00      6887437.99      1361920.26      6886687.48
      1361455.00      6885888.01
#Sta/Elev= 30
  4204.0 2186.17  4455.1 2180.87  4466.2 2180.52  4529.0 2177.67  4564.6 2176.91
  4579.8 2172.43  4596.4 2176.92  4628.2 2177.30  4641.6 2174.91  4681.3 2177.18
  4698.2 2173.12  4703.5 2176.90  4729.1 2179.06  4978.2 2176.27  4994.5 2172.02
  4994.8 2171.52  4998.8 2172.02  5011.0 2176.32  5092.0 2179.15  5393.7 2183.20
  5457.1 2181.11  5462.9 2177.36  5472.8 2178.44  5485.3 2185.44  5515.9 2181.60
  5580.4 2183.47  5589.5 2178.55  5601.9 2182.54  5636.0 2184.36  5925.0 2194.79
#Mann=8,-1,0
  4204.0    0.16       0  4455.1    0.07       0  4466.2    0.16       0
  4529.0    0.07       0  4994.5    0.07       0  4998.8    0.07       0
  5393.7    0.16       0  5636.0    0.07       0
Bank Sta=4994.5,4998.8
Exp/Cntr=0.3,0.1

Type RM Length L Ch R = 1,9796,494,494,494
BEGIN DESCRIPTION:
Sweetwater Creek Trib 27 T3_1 8.0
END DESCRIPTION:
XS GIS Cut Line= 3
      1362455.01      6887638.04      1362254.97      6886838.07
      1361454.98      6885637.97
#Sta/Elev= 30
  4175.4 2189.22  4200.6 2188.39  4283.4 2185.40  4340.4 2182.68  4399.6 2181.11
  4812.3 2176.79  4886.7 2176.30  5003.0 2173.17  5013.5 2172.46  5026.0 2169.29
  5026.4 2168.79  5031.1 2169.29  5036.1 2172.93  5043.6 2174.58  5067.6 2174.86
  5094.7 2175.68  5144.3 2175.53  5187.8 2176.91  5279.5 2177.17  5293.3 2177.36
  5389.9 2178.37  5716.3 2181.53  5749.6 2181.68  5830.2 2182.99  5914.9 2184.78
  5966.0 2187.12  5996.1 2187.12  6053.2 2189.13  6068.2 2188.70  6442.3 2204.94
#Mann=13,-1,0
  4175.4    0.07       0  4200.6    0.16       0  4283.4    0.07       0
  4812.3    0.16       0  5026.0    0.07       0  5031.1    0.16       0
  5067.6    0.07       0  5279.5    0.16       0  5293.3    0.07       0
  5389.9    0.16       0  5716.3    0.07       0  5749.6    0.16       0
  5830.2    0.07       0
Bank Sta=5026,5031.1
Exp/Cntr=0.3,0.1

Type RM Length L Ch R = 1,9302,995,995,995
BEGIN DESCRIPTION:
Sweetwater Creek Trib 27 T3_1 7.0
END DESCRIPTION:
XS GIS Cut Line= 3
      1362555.00      6887688.02      1362631.59      6886611.24
      1361855.02      6885788.02
#Sta/Elev= 30
  3920.5 2190.23  3993.3 2188.46  4211.3 2179.80  4562.1 2175.27  4756.9 2171.28
  4790.5 2172.13  4882.9 2172.44  4972.9 2170.47  4977.9 2171.09  4993.2 2167.62
  4996.6 2165.67  4997.0 2165.17  5001.7 2165.67  5006.8 2166.76  5014.1 2169.81
  5021.0 2168.44  5028.3 2169.80  5035.1 2169.36  5042.4 2170.90  5110.9 2172.88
  5159.5 2173.53  5375.0 2174.96  5694.3 2178.80  5884.3 2181.66  5933.7 2183.49
  5954.7 2183.24  5968.9 2184.48  6011.4 2185.19  6092.1 2188.58  6131.7 2190.21
#Mann=9,-1,0
  3920.5    0.07       0  4756.9    0.16       0  4790.5    0.07       0
  4996.6    0.07       0  5001.7    0.07       0  5110.9    0.16       0
  5159.5    0.07       0  5694.3    0.16       0  6092.1    0.07       0
Bank Sta=4996.6,5001.7
Exp/Cntr=0.3,0.1

Type RM Length L Ch R = 1,8307,1490,1490,1490
BEGIN DESCRIPTION:
Sweetwater Creek Trib 27 T3_1 6.0
END DESCRIPTION:
XS GIS Cut Line= 3
      1363405.00      6887637.99      1363028.70      6886814.82
      1362305.02      6885638.04
#Sta/Elev= 30
  4094.9 2193.93  4298.8 2182.64  4390.9 2179.27  4413.8 2179.50  4752.7 2170.63
  4854.2 2170.12  4953.4 2169.29  4963.5 2168.36  4977.7 2162.76  4991.3 2160.86
  4991.7 2160.36  4996.6 2160.86  4998.4 2163.68  5043.2 2168.08  5179.5 2171.21
  5210.0 2171.08  5262.6 2171.33  5318.8 2170.13  5341.9 2170.06  5363.2 2168.39
  5371.9 2169.84  5421.1 2171.63  5457.8 2171.43  5689.8 2176.45  5802.7 2177.30
  5920.4 2179.10  6215.3 2183.48  6236.6 2184.66  6347.7 2186.49  6381.5 2187.16
#Mann=11,-1,0
  4094.9    0.07       0  4854.2    0.16       0  4977.7    0.07       0
  4991.3    0.07       0  4996.6    0.07       0  5179.5    0.16       0
  5210.0    0.07       0  5318.8    0.16       0  5802.7    0.07       0
  5920.4    0.16       0  6347.7    0.07       0
Bank Sta=4991.3,4996.6
Exp/Cntr=0.3,0.1

Type RM Length L Ch R = 1,6817,498,498,498
BEGIN DESCRIPTION:
Sweetwater Creek Trib 27 T3_1 5.0
END DESCRIPTION:
XS GIS Cut Line= 3
      1363755.00      6887087.99      1363690.59      6886501.22
      1363454.97      6886237.96
#Sta/Elev= 30
  4409.7 2175.07  4520.4 2170.19  4610.9 2164.43  4819.6 2164.43  4892.6 2159.23
  4897.9 2157.79  4910.7 2155.87  4915.8 2152.93  4942.9 2153.75  4950.2 2151.70
  4950.7 2151.20  4955.6 2151.70  4963.0 2155.44  4973.1 2157.25  4983.1 2152.49
  4993.2 2152.45  4999.1 2155.53  5006.0 2157.37  5034.4 2160.00  5062.8 2159.00
  5077.0 2157.35  5084.5 2155.15  5091.2 2155.13  5098.3 2156.43  5105.4 2159.29
  5119.6 2160.95  5148.0 2163.37  5204.9 2165.30  5232.5 2166.47  5353.3 2168.29
#Mann=5,-1,0
  4409.7    0.07       0  4897.9    0.16       0  4950.2    0.07       0
  4955.6    0.16       0  5204.9    0.07       0
Bank Sta=4950.2,4955.6
Exp/Cntr=0.3,0.1

Type RM Length L Ch R = 1,6319,973,973,973
BEGIN DESCRIPTION:
Sweetwater Creek Trib 27 T3_1 4.0
END DESCRIPTION:
XS GIS Cut Line= 3
      1363954.99      6886888.04      1364020.16      6886388.48
      1363655.00      6886088.00
#Sta/Elev= 30
  4496.2 2169.04  4526.5 2168.39  4533.2 2167.32  4566.8 2165.35  4607.2 2163.52
  4612.2 2164.05  4617.3 2163.12  4686.2 2161.57  4758.4 2161.55  4778.6 2160.51
  4889.5 2162.61  4923.1 2162.17  4970.2 2158.19  4994.9 2154.42  4997.1 2153.82
  4999.4 2155.08  5004.4 2153.82  5008.2 2150.29  5008.6 2149.79  5013.6 2150.29
  5025.2 2155.85  5053.9 2156.96  5089.1 2160.25  5146.5 2160.55  5152.9 2161.39
  5181.6 2160.59  5202.4 2162.23  5224.7 2161.90  5287.0 2163.10  5472.9 2166.68
#Mann=5,-1,0
  4496.2    0.07       0  4994.9    0.16       0  5008.2    0.07       0
  5013.6    0.16       0  5287.0    0.07       0
Bank Sta=5008.2,5013.6
Exp/Cntr=0.3,0.1

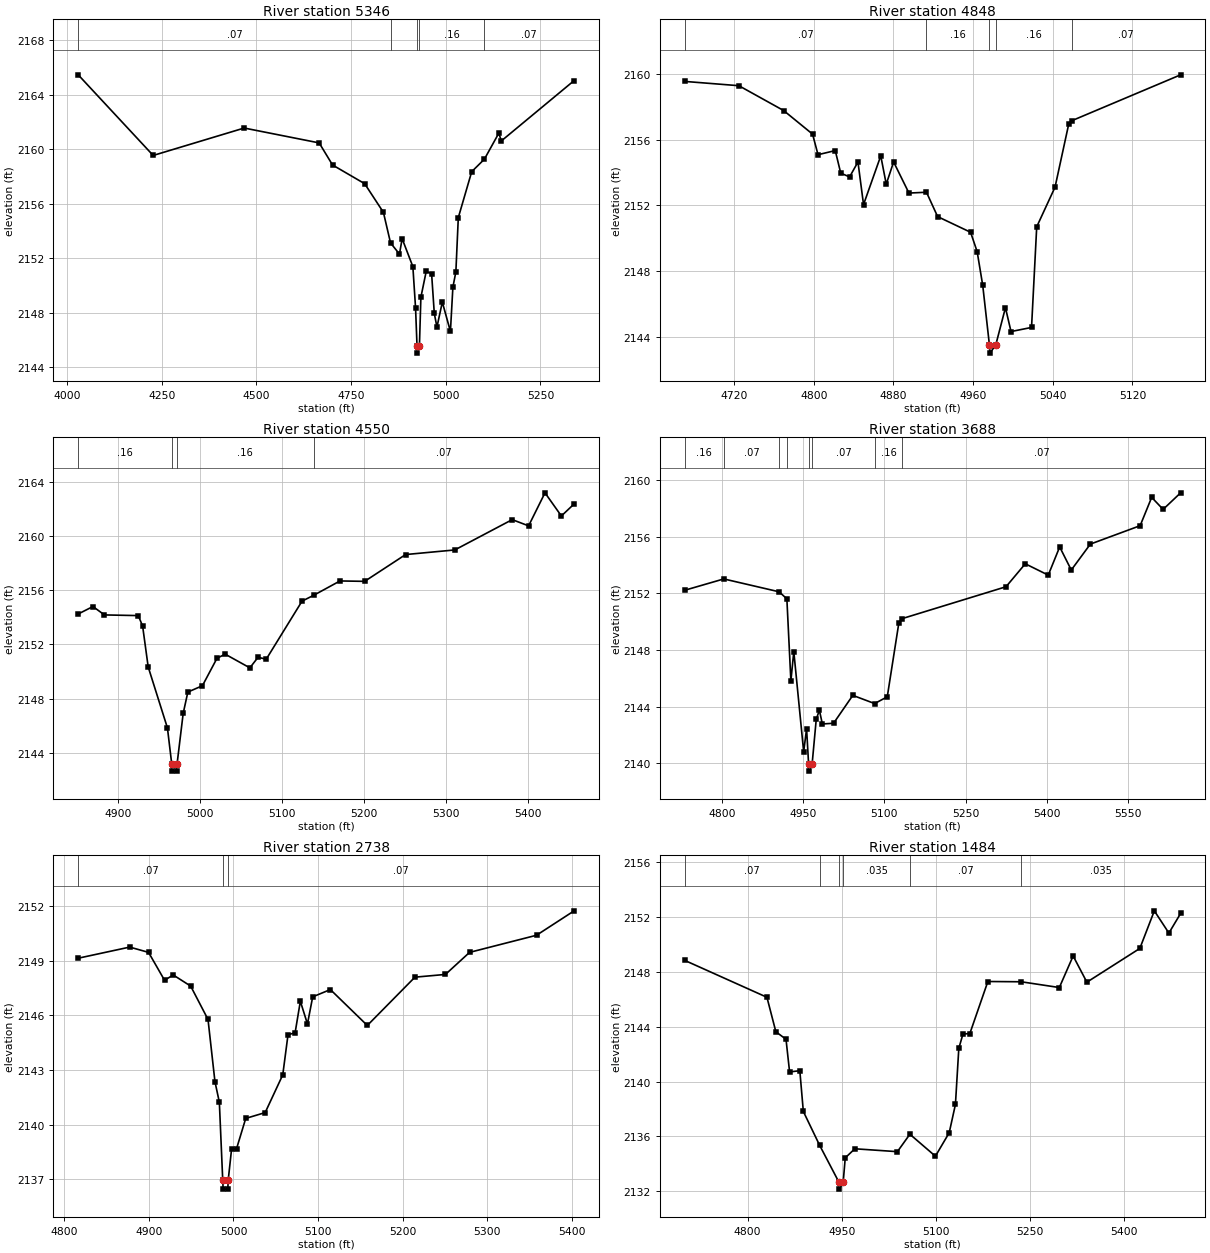
Type RM Length L Ch R = 1,5346,498,498,498
BEGIN DESCRIPTION:
Sweetwater Creek Trib 27 T3_1 3.0
END DESCRIPTION:
XS GIS Cut Line= 3
      1364005.00      6886788.00      1364691.10      6886101.19
      1364904.97      6885838.04
#Sta/Elev= 30
  4029.2 2165.45  4227.2 2159.54  4467.6 2161.55  4665.6 2160.46  4701.0 2158.84
  4785.8 2157.47  4835.3 2155.37  4854.1 2153.13  4877.7 2152.31  4884.8 2153.44
  4913.1 2151.39  4920.2 2148.37  4924.1 2145.55  4924.6 2145.05  4930.4 2145.55
  4934.3 2149.15  4948.4 2151.05  4962.6 2150.87  4969.7 2147.96  4976.7 2146.96
  4990.9 2148.79  5012.3 2146.64  5018.8 2149.88  5026.7 2151.01  5033.1 2154.98
  5068.5 2158.35  5102.1 2159.27  5140.2 2161.18  5146.6 2160.60  5339.1 2165.03
#Mann=5,-1,0
  4029.2    0.07       0  4854.1    0.16       0  4924.1    0.07       0
  4930.4    0.16       0  5102.1    0.07       0
Bank Sta=4924.1,4930.4
Exp/Cntr=0.3,0.1

Type RM Length L Ch R = 1,4848,298,298,298
BEGIN DESCRIPTION:
Sweetwater Creek Trib 27 T3_1 2.0
END DESCRIPTION:
XS GIS Cut Line= 3
      1364654.98      6886388.01      1364953.50      6886248.28
      1365005.01      6886087.95
#Sta/Elev= 30
  4670.4 2159.53  4724.8 2159.27  4769.8 2157.76  4798.8 2156.33  4804.3 2155.08
  4821.6 2155.33  4827.1 2153.96  4836.0 2153.73  4844.4 2154.64  4850.0 2152.05
  4867.3 2155.01  4872.8 2153.29  4880.2 2154.64  4895.6 2152.75  4913.2 2152.80
  4924.4 2151.32  4957.5 2150.37  4964.1 2149.19  4969.7 2147.14  4976.4 2143.53
  4976.9 2143.03  4982.8 2143.53  4992.5 2145.79  4998.1 2144.34  5018.7 2144.59
  5023.9 2150.70  5042.3 2153.11  5056.0 2156.93  5059.0 2157.14  5168.4 2159.93
#Mann=5,-1,0
  4670.4    0.07       0  4913.2    0.16       0  4976.4    0.07       0
  4982.8    0.16       0  5059.0    0.07       0
Bank Sta=4976.4,4982.8
Exp/Cntr=0.3,0.1

Type RM Length L Ch R = 1,4550,862,862,862
BEGIN DESCRIPTION:
Sweetwater Creek Trib 27 T3_1 4038
END DESCRIPTION:
XS GIS Cut Line= 3
      1365072.94      6886557.96      1365125.12      6886418.60
      1365143.21      6885962.46
#Sta/Elev= 30
  4851.2 2154.25  4869.2 2154.80  4883.2 2154.18  4924.5 2154.13  4929.8 2153.36
  4936.6 2150.34  4960.1 2145.83  4965.4 2143.14  4965.9 2142.64  4971.3 2142.64
  4971.8 2143.14  4979.3 2146.90  4985.0 2148.48  5002.8 2148.95  5020.6 2150.98
  5030.6 2151.28  5060.7 2150.27  5070.7 2151.05  5080.7 2150.91  5124.4 2155.20
  5138.6 2155.63  5170.7 2156.69  5200.8 2156.66  5250.8 2158.64  5310.8 2158.98
  5380.9 2161.22  5400.9 2160.76  5420.9 2163.20  5440.9 2161.49  5456.5 2162.38
#Mann=4,-1,0
  4851.2    0.16       0  4965.4    0.07       0  4971.8    0.16       0
  5138.6    0.07       0
Bank Sta=4965.4,4971.8
Exp/Cntr=0.3,0.1

Type RM Length L Ch R = 1,3688,950,950,950
BEGIN DESCRIPTION:
Sweetwater Creek Trib 27 T3_1 4037
END DESCRIPTION:
XS GIS Cut Line= 3
      1365642.12      6886691.28      1365747.65      6886444.39
      1365280.82      6885996.71
#Sta/Elev= 30
  4731.5 2152.21  4803.7 2153.01  4906.0 2152.10  4920.1 2151.60  4927.5 2145.81
  4932.9 2147.88  4951.1 2140.81  4956.5 2142.43  4960.2 2139.94  4960.7 2139.44
  4966.7 2139.94  4974.3 2143.10  4980.1 2143.74  4985.6 2142.77  5006.3 2142.82
  5041.8 2144.79  5082.1 2144.21  5105.4 2144.69  5126.7 2149.89  5133.0 2150.21
  5324.6 2152.46  5360.1 2154.08  5402.5 2153.28  5423.6 2155.27  5445.0 2153.64
  5480.2 2155.47  5572.1 2156.77  5593.4 2158.77  5614.5 2157.92  5646.8 2159.09
#Mann=8,-1,0
  4731.5    0.16       0  4803.7    0.07       0  4906.0    0.16       0
  4920.1    0.07       0  4960.2    0.07       0  4966.7    0.07       0
  5082.1    0.16       0  5133.0    0.07       0
Bank Sta=4960.2,4966.7
Exp/Cntr=0.3,0.1

Type RM Length L Ch R = 1,2738,1254,1254,1254
BEGIN DESCRIPTION:
Sweetwater Creek Trib 27 T3_1 4036
END DESCRIPTION:
XS GIS Cut Line= 3
      1366218.72      6886347.24      1366175.58      6886168.78
      1365934.40      6885846.04
#Sta/Elev= 30
  4816.4 2149.13  4877.3 2149.74  4899.6 2149.45  4918.5 2147.92  4928.8 2148.21
  4949.4 2147.60  4969.9 2145.77  4978.1 2142.36  4983.3 2141.23  4987.3 2136.96
  4987.8 2136.46  4993.3 2136.46  4993.8 2136.96  4997.8 2138.67  5003.6 2138.67
  5014.5 2140.34  5037.5 2140.66  5058.3 2142.73  5064.5 2144.93  5072.9 2145.04
  5079.1 2146.77  5087.5 2145.52  5093.7 2147.01  5114.6 2147.41  5158.3 2145.44
  5214.6 2148.09  5250.7 2148.24  5279.2 2149.45  5358.4 2150.39  5402.9 2151.73
#Mann=3,-1,0
  4816.4    0.07       0  4987.3    0.07       0  4993.8    0.07       0
Bank Sta=4987.3,4993.8
Exp/Cntr=0.3,0.1

Type RM Length L Ch R = 1,1484,615,615,615
BEGIN DESCRIPTION:
Sweetwater Creek Trib 27 T3_1 1.0
END DESCRIPTION:
XS GIS Cut Line= 3
      1366847.19      6885793.58      1366705.46      6885528.72
      1366258.85      6885327.12
#Sta/Elev= 30
  4699.6 2148.83  4830.7 2146.14  4844.9 2143.63  4861.1 2143.08  4866.8 2140.70
  4883.1 2140.79  4888.7 2137.82  4914.5 2135.37  4945.5 2132.66  4946.0 2132.16
  4952.2 2132.66  4955.5 2134.44  4970.8 2135.10  5038.6 2134.89  5058.5 2136.16
  5099.2 2134.56  5121.2 2136.27  5131.1 2138.33  5136.5 2142.42  5143.1 2143.46
  5154.1 2143.50  5182.8 2147.29  5235.9 2147.27  5296.7 2146.85  5318.7 2149.15
  5340.6 2147.24  5425.0 2149.70  5448.1 2152.44  5471.3 2150.82  5490.0 2152.25
#Mann=6,-1,0
  4699.6    0.07       0  4914.5   0.035       0  4945.5   0.035       0
  4952.2   0.035       0  5058.5    0.07       0  5235.9   0.035       0
Bank Sta=4945.5,4952.2
Exp/Cntr=0.3,0.1

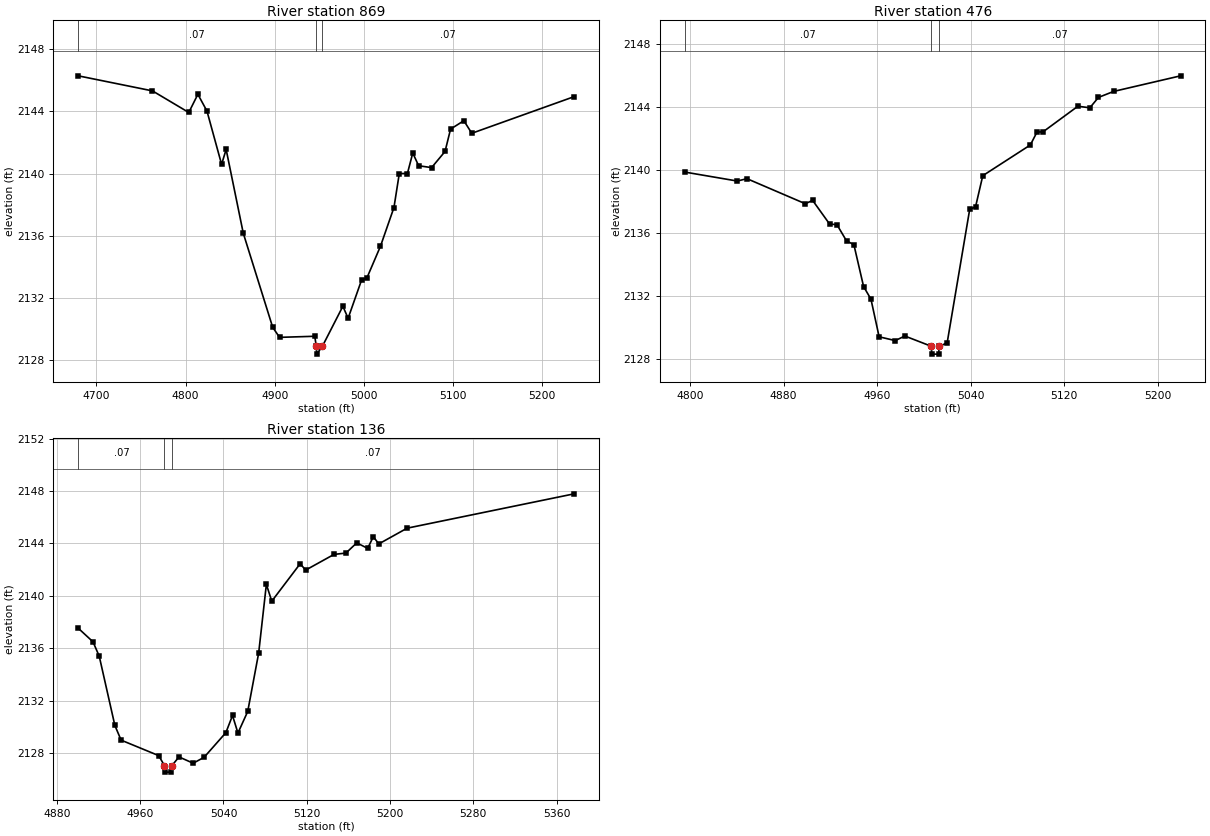
Type RM Length L Ch R = 1,869,393,393,393
BEGIN DESCRIPTION:
Sweetwater Creek Trib 27 T3_1 2221
END DESCRIPTION:
XS GIS Cut Line= 3
      1367080.26      6885549.84      1367026.08      6885264.84
      1366880.93      6885041.81
#Sta/Elev= 30
  4679.5 2146.29  4762.8 2145.32  4803.5 2143.93  4813.7 2145.10  4823.9 2144.02
  4840.3 2140.59  4845.4 2141.55  4864.6 2136.16  4897.6 2130.10  4905.3 2129.45
  4944.8 2129.52  4946.5 2128.87  4947.0 2128.37  4953.3 2128.87  4976.3 2131.45
  4982.2 2130.68  4997.4 2133.16  5003.3 2133.28  5018.5 2135.32  5033.6 2137.81
  5039.6 2140.00  5048.7 2140.00  5054.7 2141.32  5061.3 2140.50  5075.8 2140.38
  5090.9 2141.42  5097.1 2142.86  5112.0 2143.40  5120.9 2142.59  5235.7 2144.95
#Mann=3,-1,0
  4679.5    0.07       0  4946.5    0.07       0  4953.3    0.07       0
Bank Sta=4946.5,4953.3
Exp/Cntr=0.3,0.1

Type RM Length L Ch R = 1,476,340,340,340
BEGIN DESCRIPTION:
 Sweetwater Creek Trib 27 T3_1 4180
END DESCRIPTION:
XS GIS Cut Line= 3
      1367267.37      6885039.13      1367104.57      6884915.05
      1366888.63      6884955.55
#Sta/Elev= 30
  4795.3 2139.90  4840.3 2139.33  4848.6 2139.48  4898.5 2137.89  4904.8 2138.10
  4919.3 2136.60  4925.6 2136.56  4933.8 2135.53  4940.1 2135.29  4948.4 2132.63
  4954.7 2131.83  4961.7 2129.44  4975.5 2129.20  4983.7 2129.49  5006.3 2128.84
  5006.8 2128.34  5012.6 2128.34  5013.1 2128.84  5019.9 2129.05  5039.2 2137.53
  5044.2 2137.69  5050.4 2139.67  5091.1 2141.62  5096.8 2142.44  5101.9 2142.45
  5131.8 2144.08  5142.0 2143.98  5149.4 2144.64  5162.4 2145.02  5219.7 2146.01
#Mann=3,-1,0
  4795.3    0.07       0  5006.3    0.07       0  5013.1    0.07       0
Bank Sta=5006.3,5013.1
Exp/Cntr=0.3,0.1

Type RM Length L Ch R = 1,136,0,0,0
BEGIN DESCRIPTION:
Sweetwater Creek Trib 27 T3_1 4181
END DESCRIPTION:
XS GIS Cut Line= 3
      1367329.93      6884971.40      1367384.83      6884888.42
      1367272.60      6884528.72
#Sta/Elev= 30
  4900.5 2137.53  4914.7 2136.49  4920.7 2135.39  4935.7 2130.11  4941.7 2128.99
  4977.8 2127.81  4983.3 2127.05  4983.8 2126.55  4990.0 2126.55  4990.5 2127.05
  4997.3 2127.71  5010.9 2127.23  5021.4 2127.68  5042.3 2129.56  5048.7 2130.87
  5053.9 2129.53  5063.3 2131.18  5073.8 2135.63  5081.2 2140.87  5086.4 2139.59
  5113.7 2142.45  5118.9 2141.96  5146.2 2143.16  5157.6 2143.26  5168.0 2144.04
  5178.5 2143.62  5183.9 2144.51  5189.2 2143.96  5216.4 2145.16  5376.8 2147.78
#Mann=3,-1,0
  4900.5    0.07       0  4983.3    0.07       0  4990.5    0.07       0
Bank Sta=4983.3,4990.5
Exp/Cntr=0.3,0.1

Chan Stop Cuts=-1