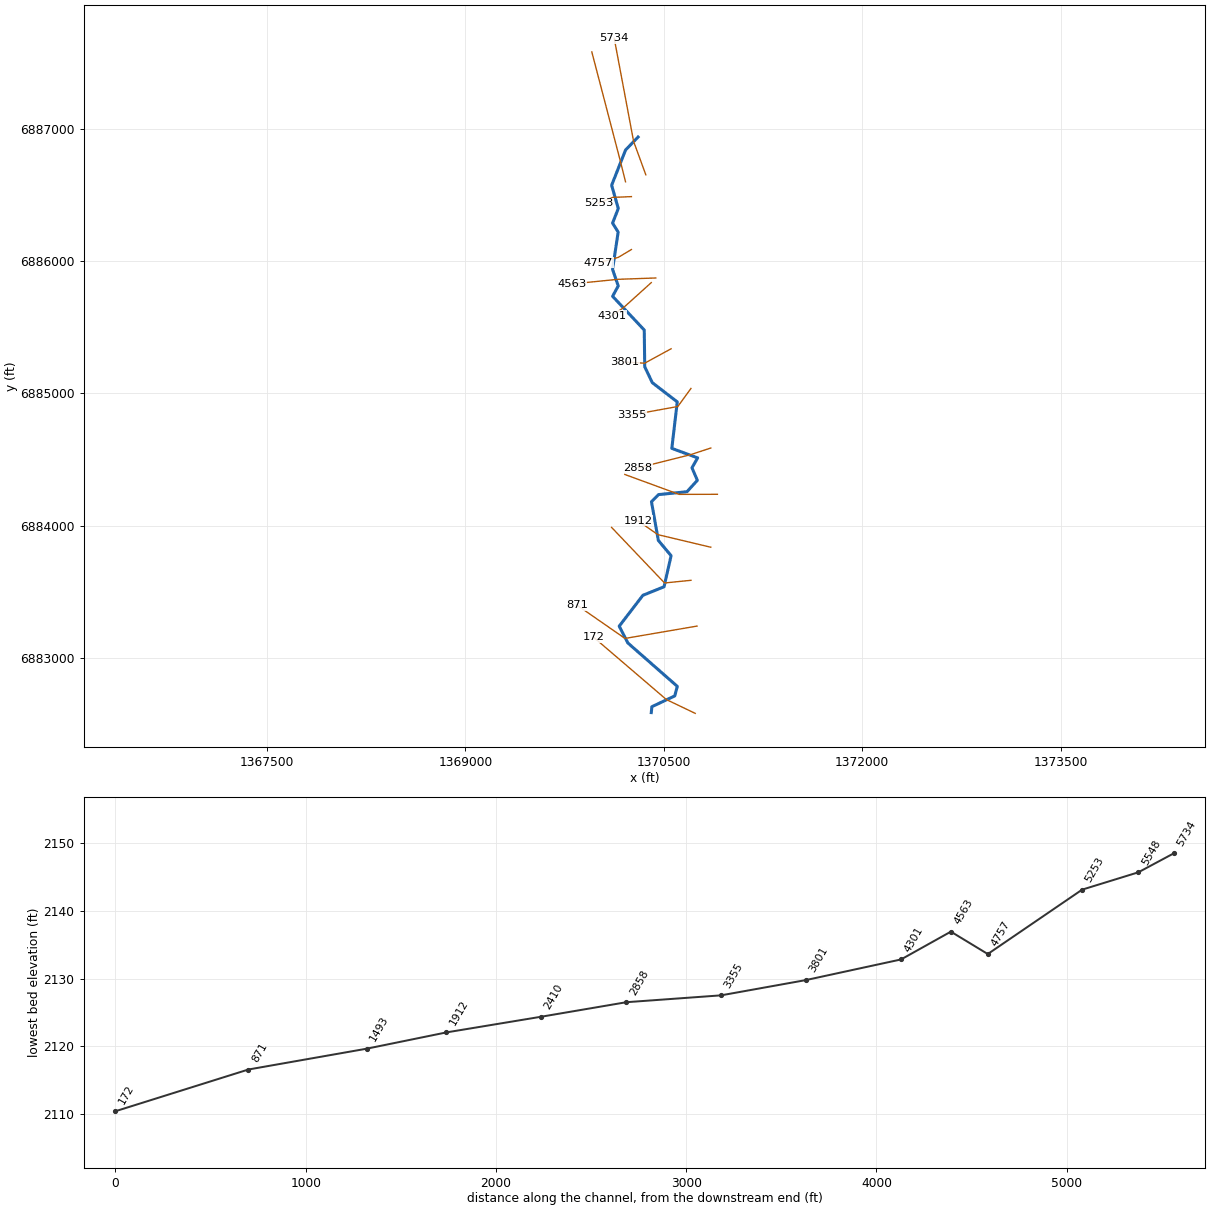
--- Sweetwater Creek Trib 27 T3_2.prj (project) ---

Proj Title=Sweetwater Creek Trib 27 T3_2 Base Level Engineering
Current Plan=p01
Default Exp/Contr=0.3,0.1
English Units
Geom File=g01
Flow File=f01
Plan File=p01
Y Axis Title=Elevation
X Axis Title(PF)=Main Channel Distance
X Axis Title(XS)=Station
BEGIN DESCRIPTION:
Sweetwater Creek Trib 27 T3_2
END DESCRIPTION:
DSS Export Rating Curves= 0
DSS Export Rating Curve Sorted= 0
DSS Export Volume Flow Curves= 0
DXF OffsetX= 0
DXF OffsetY= 0
DXF ScaleX= 1
DXF ScaleY= 10

--- Sweetwater Creek Trib 27 T3_2.p01 (plan) ---

Plan Title=Multiple Run
Short Identifier=Multiple
Geom File=g01
Flow File=f01
Subcritical Flow
K Sum by GR= 0
Std Step Tol= 0.01
Critical Tol= 0.01
Num of Std Step Trials= 20
Max Error Tol= 0.3
Flow Tol Ratio= 0.001
Split Flow NTrial= 30
Split Flow Tol= 0.02
Split Flow Ratio= 0.02
Log Output Level= 0
Friction Slope Method= 1
Unsteady Friction Slope Method= 2
Unsteady Bridges Friction Slope Method= 1
Parabolic Critical Depth
Global Vel Dist=  1 , 1 , 1
Global Log Level= 0
CheckData=True
Encroach Param= -1, 0, 0, 0
BEGIN DESCRIPTION:
Multiple Run
END DESCRIPTION:

--- Sweetwater Creek Trib 27 T3_2.f01 (steady flow) ---

Flow Title=Multiple
Number of Profiles=7
Profile Names=10-year,25-year,50-year,1pct_min,100-year,1pct_plu,500-year
River Rch & RM= Sweetwater Creek,Reach-1,5734
     286     408     512     320     639    1274    1005
River Rch & RM= Sweetwater Creek,Reach-1,4757
     287     407     508     315     629    1255     977
Boundary for River Rch & Prof#=Sweetwater Creek,Reach-1,1
Up Type=0
Dn Type=3
Dn Slope=0.005
Boundary for River Rch & Prof#=Sweetwater Creek,Reach-1,2
Up Type=0
Dn Type=3
Dn Slope=0.005
Boundary for River Rch & Prof#=Sweetwater Creek,Reach-1,3
Up Type=0
Dn Type=3
Dn Slope=0.005
Boundary for River Rch & Prof#=Sweetwater Creek,Reach-1,4
Up Type=0
Dn Type=3
Dn Slope=0.005
Boundary for River Rch & Prof#=Sweetwater Creek,Reach-1,5
Up Type=0
Dn Type=3
Dn Slope=0.005
Boundary for River Rch & Prof#=Sweetwater Creek,Reach-1,6
Up Type=0
Dn Type=3
Dn Slope=0.005
Boundary for River Rch & Prof#=Sweetwater Creek,Reach-1,7
Up Type=0
Dn Type=3
Dn Slope=0.005

--- Sweetwater Creek Trib 27 T3_2.g01 (geometry) ---

Geom Title=Existing Conditions
Program Version=4.10

River Reach=Sweetwater Creek,Reach-1
Reach XY= 30
        1370305.        6886938.      1370210.79      6886840.32
      1370105.55      6886574.03      1370155.75      6886398.04
      1370112.56        6886288.      1370154.67      6886219.78
      1370112.56        6885938.       1370155.3      6885812.96
      1370112.81      6885734.59      1370351.93       6885479.7
      1370355.67      6885201.91      1370413.02      6885081.66
      1370601.54      6884936.52      1370560.34      6884585.26
      1370755.53      6884513.29      1370712.64      6884438.03
      1370753.35      6884344.04      1370675.21      6884257.59
      1370460.21      6884235.91      1370406.53      6884182.17
      1370458.55      6883889.47       1370554.9      6883773.96
      1370501.56      6883539.23      1370341.67      6883474.61
      1370162.78       6883241.4        1370228.      6883114.53
      1370601.92      6882786.34      1370582.45      6882714.16
       1370409.9      6882632.72        1370405.        6882588.

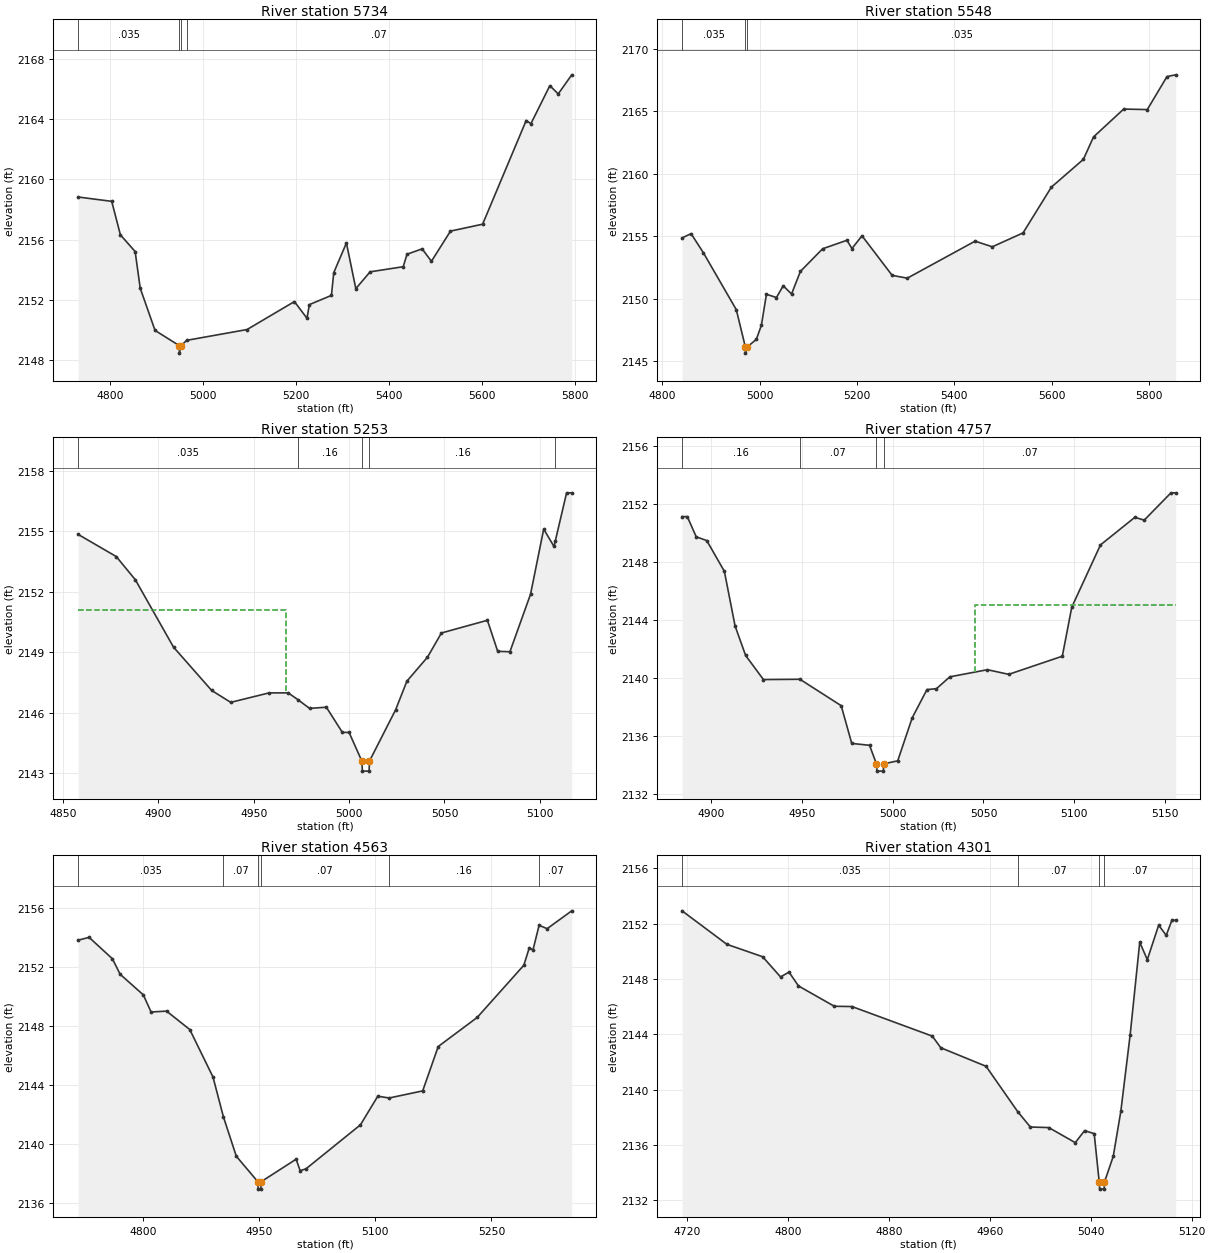
Type RM Length L Ch R = 1 ,5734    ,186,186,186
BEGIN DESCRIPTION:
Sweetwater Creek Trib 27 T3_2 9.0
END DESCRIPTION:
XS GIS Cut Line= 3
       1370363.9      6886652.57      1370271.64      6886904.83
      1370125.11      6887684.28
#Sta/Elev= 30
  4731.4 2158.83  4803.7 2158.54  4822.4 2156.31  4854.1  2155.2    4865 2152.76
  4896.9 2149.95    4949 2148.94  4949.3 2148.44    4953 2148.94  4964.8 2149.29
  5094.8 2150.01  5196.6 2151.87  5223.7 2150.76  5228.8 2151.67  5276.2 2152.28
  5281.3  2153.8  5308.5 2155.77  5328.7 2152.73  5359.4 2153.85  5430.6 2154.19
  5438.8 2155.02  5471.3 2155.38  5491.3 2154.55  5532.3 2156.56  5601.4 2157.02
  5695.1 2163.92  5705.3 2163.71    5746 2166.24    5764 2165.69  5793.1 2166.96
#Mann= 4 ,-1 , 0
  4731.4    .035       0    4949     .07       0    4953    .035       0
  4964.8     .07       0
Bank Sta=4949,4953
XS Rating Curve= 0 ,0
Exp/Cntr=0.3,0.1

Type RM Length L Ch R = 1 ,5548    ,295,295,295
BEGIN DESCRIPTION:
Sweetwater Creek Trib 27 T3_2 4035
END DESCRIPTION:
XS GIS Cut Line= 3
      1370210.41      6886599.94      1370171.83       6886754.6
      1369955.74      6887581.33
#Sta/Elev= 30
  4840.6 2154.87  4859.2 2155.21  4884.3 2153.69    4952 2149.13  4970.6 2146.15
  4970.8 2145.65  4974.6 2146.15  4993.2 2146.75  5003.6 2147.88  5013.9 2150.36
  5034.5  2150.1  5048.4 2151.04  5065.5 2150.38  5083.7 2152.19  5129.3    2154
  5179.2 2154.68  5189.6 2154.02  5210.2 2155.04  5272.2 2151.87  5303.3 2151.65
  5442.5 2154.61  5477.8 2154.16    5541 2155.27  5599.1 2158.93    5665 2161.16
  5685.7 2162.95  5747.7 2165.18  5796.2 2165.14  5836.6 2167.78  5854.5 2167.92
#Mann= 3 ,-1 , 0
  4840.6    .035       0  4970.6    .035       0  4974.6    .035       0
Bank Sta=4970.6,4974.6
XS Rating Curve= 0 ,0
Exp/Cntr=0.3,0.1

Type RM Length L Ch R = 1 ,5253    ,496,496,496
BEGIN DESCRIPTION:
Sweetwater Creek Trib 27 T3_2 8.0
END DESCRIPTION:
XS GIS Cut Line= 3
      1370254.97        6886488.       1370113.1      6886481.96
      1370004.99        6886438.
#Sta/Elev= 30
    4858 2154.84    4878 2153.74    4888 2152.59    4908 2149.25    4928  2147.1
    4938 2146.51  4958.1 2146.98  4968.1 2146.98  4973.4 2146.63  4979.3 2146.21
  4988.1 2146.27  4996.5 2145.02    5000 2145.02  5006.7  2143.6    5007  2143.1
  5010.5  2143.1  5010.7  2143.6  5024.4 2146.14  5030.3 2147.56  5041.1 2148.75
  5048.4 2149.95  5072.5 2150.58  5077.9 2149.04  5084.3 2149.02  5095.1 2151.87
    5102  2155.1  5107.4 2154.24  5108.1 2154.52    5114  2156.9  5116.7  2156.9
#Mann= 5 ,-1 , 0
    4858    .035       0  4973.4     .16       0  5006.7     .07       0
  5010.7     .16       0  5108.1     .07       0
#XS Ineff= 2 , 0
         4966.95 2151.09
Permanent Ineff=
       F       F
Bank Sta=5006.7,5010.7
XS Rating Curve= 0 ,0
Exp/Cntr=0.3,0.1

Type RM Length L Ch R = 1 ,4757    ,194,194,194
BEGIN DESCRIPTION:
Sweetwater Creek Trib 27 T3_2 7.0
END DESCRIPTION:
XS GIS Cut Line= 3
      1370254.99      6886087.99       1370155.4       6886028.7
      1370005.01        6885988.
#Sta/Elev= 30
  4884.1 2151.15    4887 2151.15  4891.9 2149.76  4897.7  2149.5  4907.4 2147.38
  4913.3 2143.61  4919.1 2141.58  4928.9 2139.92    4949 2139.94  4971.7 2138.12
  4977.5 2135.52  4987.3 2135.39  4991.1 2134.11  4991.4 2133.61  4994.9 2133.61
  4995.1 2134.11  5002.8 2134.32  5010.8 2137.29  5018.9 2139.23  5024.1 2139.29
  5031.5 2140.11  5052.2  2140.6  5063.9 2140.28  5093.4 2141.53  5098.6 2144.91
  5114.4  2149.2  5133.3  2151.1  5138.5 2150.91  5153.2 2152.79  5155.8 2152.79
#Mann= 4 ,-1 , 0
  4884.1     .16       0    4949     .07       0  4991.1     .07       0
  4995.1     .07       0
#XS Ineff= 2 , 0
                         5045.43         2145.07
Permanent Ineff=
       F       F
Bank Sta=4991.1,4995.1
XS Rating Curve= 0 ,0
Exp/Cntr=0.3,0.1

Type RM Length L Ch R = 1 ,4563    ,262,262,262
BEGIN DESCRIPTION:
Sweetwater Creek Trib 27 T3_2 4034
END DESCRIPTION:
XS GIS Cut Line= 3
      1370439.22      6885873.07       1370155.3      6885863.03
      1369803.37      6885827.69
#Sta/Elev= 30
  4715.9 2153.79  4730.1 2153.98  4760.2 2152.53  4770.2 2151.48  4800.2 2150.08
  4810.2 2148.92  4830.2 2148.98  4860.2 2147.73  4890.2 2144.51  4903.6 2141.82
  4920.3 2139.14  4948.2 2137.41  4948.5 2136.91  4952.1 2136.91  4952.3 2137.41
  4997.6 2138.94  5002.8 2138.16  5010.4 2138.29  5080.7 2141.27  5103.1 2143.21
  5117.8 2143.09  5161.1 2143.57  5181.2 2146.58  5231.5 2148.55  5291.8 2152.09
  5298.7 2153.25  5303.7 2153.14  5311.5  2154.8  5321.9 2154.57  5353.7 2155.78
#Mann= 6 ,-1 , 0
  4715.9    .035       0  4903.6     .07       0  4948.2     .07       0
  4952.3     .07       0  5117.8     .16       0  5311.5     .07       0
Bank Sta=4948.2,4952.3
XS Rating Curve= 0 ,0
Exp/Cntr=0.3,0.1

Type RM Length L Ch R = 1 ,4301    ,500,500,500
BEGIN DESCRIPTION:
Sweetwater Creek Trib 27 T3_2 6.0
END DESCRIPTION:
XS GIS Cut Line= 3
      1370404.98      6885837.98      1370194.17      6885647.68
        1370105.        6885588.
#Sta/Elev= 30
    4716 2152.93  4751.5 2150.51  4779.9 2149.61  4794.1 2148.15  4800.8  2148.5
  4808.3  2147.5  4836.7 2146.03  4850.7 2146.01  4914.4 2143.87  4921.1 2143.03
    4957 2141.69    4982 2138.42  4992.1  2137.3  5006.7 2137.26  5027.7 2136.17
  5035.1 2137.04  5042.7 2136.82  5046.7 2133.31    5047 2132.81  5050.6 2132.81
  5050.8 2133.31  5057.8 2135.18  5063.8 2138.43  5071.2 2143.96  5078.8 2150.66
  5084.8  2149.4  5093.8 2151.89  5099.8 2151.16  5104.3 2152.25  5107.3 2152.25
#Mann= 4 ,-1 , 0
    4716    .035       0    4982     .07       0  5046.7     .07       0
  5050.8     .07       0
Bank Sta=5046.7,5050.8
XS Rating Curve= 0 ,0
Exp/Cntr=0.3,0.1

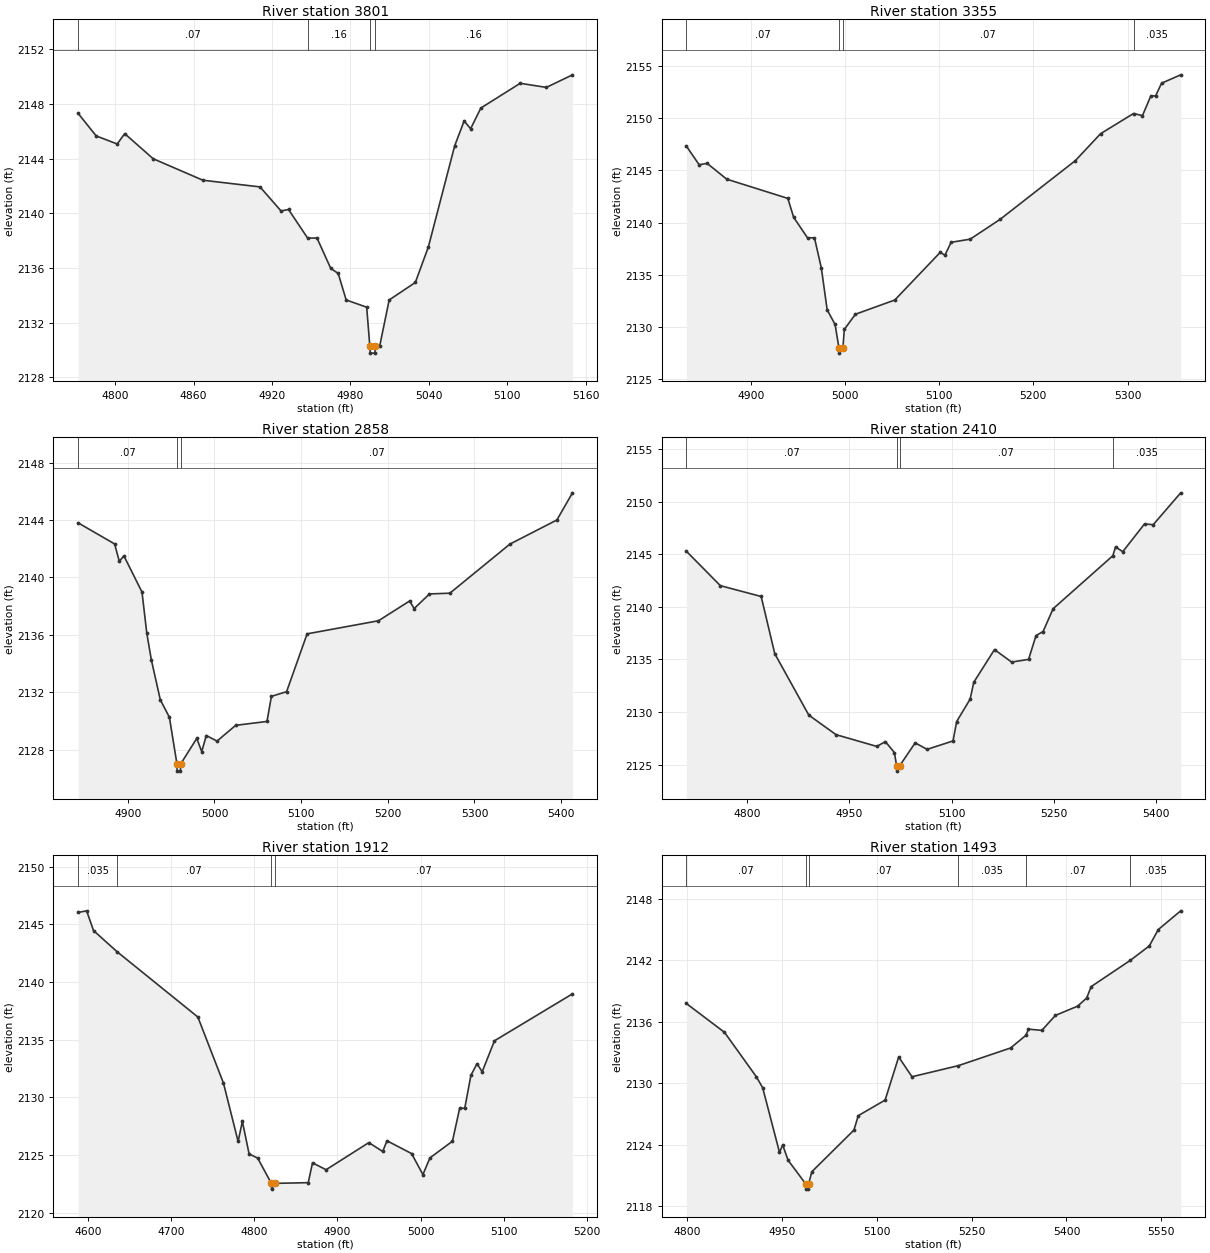
Type RM Length L Ch R = 1 ,3801    ,446,446,446
BEGIN DESCRIPTION:
Sweetwater Creek Trib 27 T3_2 5.0
END DESCRIPTION:
XS GIS Cut Line= 3
      1370554.99        6885338.      1370354.54      6885228.72
      1370205.03        6885238.
#Sta/Elev= 30
  4771.7 2147.31  4785.5 2145.66  4801.6 2145.07  4807.3 2145.83  4829.1 2143.99
  4867.1 2142.42  4910.8 2141.93  4926.9 2140.17  4932.6 2140.28  4947.2 2138.19
  4954.4 2138.19  4964.9 2135.97  4970.6  2135.6  4976.7 2133.66  4992.4 2133.13
  4994.8 2130.27  4995.1 2129.77  4998.7 2129.77    4999 2130.27  5002.3 2130.27
  5009.6 2133.66  5029.6 2134.94  5039.6 2137.55  5059.7 2144.94  5066.9 2146.75
  5071.9 2146.19  5079.7  2147.7  5109.8 2149.51  5129.8 2149.21  5149.8 2150.13
#Mann= 4 ,-1 , 0
  4771.7     .07       0  4947.2     .16       0  4994.8     .07       0
    4999     .16       0
Bank Sta=4994.8,4999
XS Rating Curve= 0 ,0
Exp/Cntr=0.3,0.1

Type RM Length L Ch R = 1 ,3355    ,497,497,497
BEGIN DESCRIPTION:
Sweetwater Creek Trib 27 T3_2 4.0
END DESCRIPTION:
XS GIS Cut Line= 3
      1370705.02      6885038.03      1370605.79      6884901.72
      1370255.03      6884838.01
#Sta/Elev= 30
  4831.4 2147.33    4845 2145.54  4853.5 2145.67  4874.3 2144.16  4939.2 2142.32
  4945.4 2140.51  4960.1 2138.55  4967.5 2138.55  4974.8 2135.66    4981 2131.66
  4989.4 2130.26  4993.5 2128.02  4993.8 2127.52  4997.7 2128.02  4999.2 2129.79
    5011 2131.24  5052.8  2132.6  5101.1 2137.16  5106.1 2136.89  5112.6 2138.12
  5132.9 2138.42  5164.6 2140.31  5244.7 2145.94  5271.4 2148.51  5306.4 2150.44
  5315.9 2150.24  5324.8 2152.13  5329.8 2152.12  5336.2 2153.34  5356.5 2154.14
#Mann= 4 ,-1 , 0
  4831.4     .07       0  4993.5     .07       0  4997.7     .07       0
  5306.4    .035       0
Bank Sta=4993.5,4997.7
XS Rating Curve= 0 ,0
Exp/Cntr=0.3,0.1

Type RM Length L Ch R = 1 ,2858    ,448,448,448
BEGIN DESCRIPTION:
Sweetwater Creek Trib 27 T3_2 3.0
END DESCRIPTION:
XS GIS Cut Line= 3
      1370854.97      6884587.99      1370705.66      6884538.51
      1370304.98      6884437.99
#Sta/Elev= 30
  4842.7  2143.8  4884.8 2142.33  4890.2 2141.12  4895.5  2141.5  4916.4 2138.98
  4921.9 2136.12  4927.2 2134.25  4937.5 2131.48    4948 2130.26  4956.7 2127.01
    4957 2126.51  4960.7 2126.51    4961 2127.01  4979.6 2128.79  4985.3 2127.87
  4990.6 2128.99  5002.9  2128.6  5024.5  2129.7  5060.6 2129.97  5065.7 2131.72
  5083.2 2132.04  5106.9 2136.07  5189.2 2136.98  5225.2 2138.36  5230.4 2137.83
  5248.1 2138.85  5271.6  2138.9  5340.9 2142.32  5395.1    2144  5413.1 2145.89
#Mann= 3 ,-1 , 0
  4842.7     .07       0  4956.7     .07       0    4961     .07       0
Bank Sta=4956.7,4961
XS Rating Curve= 0 ,0
Exp/Cntr=0.3,0.1

Type RM Length L Ch R = 1 ,2410    ,498,498,498
BEGIN DESCRIPTION:
Sweetwater Creek Trib 27 T3_2 2.0
END DESCRIPTION:
XS GIS Cut Line= 3
      1370905.01        6884238.      1370615.21       6884237.5
      1370205.04      6884387.99
#Sta/Elev= 30
  4710.2 2145.29  4760.2 2142.01  4820.2 2140.98  4840.2 2135.54  4890.2  2129.7
  4930.2 2127.84  4990.2 2126.72  5002.8 2127.18  5016.1 2126.13  5019.3 2124.87
  5019.6 2124.37  5023.7 2124.87  5046.6 2127.06  5064.1 2126.44  5102.2 2127.24
  5107.6 2129.09  5127.4 2131.22  5132.7 2132.82  5163.2 2135.93  5188.4 2134.74
  5213.3    2135  5224.2 2137.26  5234.6 2137.65  5249.4 2139.82  5337.2 2144.86
  5341.1  2145.7  5351.7 2145.24  5383.7 2147.88  5396.5 2147.81  5436.9 2150.84
#Mann= 4 ,-1 , 0
  4710.2     .07       0  5019.3     .07       0  5023.7     .07       0
  5337.2    .035       0
Bank Sta=5019.3,5023.7
XS Rating Curve= 0 ,0
Exp/Cntr=0.3,0.1

Type RM Length L Ch R = 1 ,1912    ,419,419,419
BEGIN DESCRIPTION:
Sweetwater Creek Trib 27 T3_2 1.0
END DESCRIPTION:
XS GIS Cut Line= 3
      1370854.96      6883838.01      1370454.53      6883933.26
      1370304.97      6884038.02
#Sta/Elev= 30
  4588.4 2146.03  4598.6 2146.17  4606.9 2144.46    4635 2142.64  4732.3 2136.97
  4763.1 2131.24  4780.7 2126.19  4785.8 2127.93  4793.9 2125.11  4804.2 2124.75
  4820.6 2122.56  4820.9 2122.06    4825 2122.56    4865 2122.62  4870.1 2124.34
  4886.4 2123.74  4937.8 2126.09  4954.5 2125.32  4959.6 2126.25  4989.2 2125.14
  5002.8 2123.32  5011.3 2124.77  5038.3 2126.21    5047 2129.07  5053.1 2129.07
  5060.5 2131.92  5067.9 2132.93    5074 2132.22  5088.8 2134.91  5182.6 2138.98
#Mann= 4 ,-1 , 0
  4588.4    .035       0    4635     .07       0  4820.6     .07       0
    4825     .07       0
Bank Sta=4820.6,4825
XS Rating Curve= 0 ,0
Exp/Cntr=0.3,0.1

Type RM Length L Ch R = 1 ,1493    ,622,622,622
BEGIN DESCRIPTION:
Sweetwater Creek Trib 27 T3_2 2027
END DESCRIPTION:
XS GIS Cut Line= 3
      1370705.01        6883588.      1370505.43      6883567.76
      1370104.98      6883988.02
#Sta/Elev= 30
  4799.4  2137.8  4859.7 2134.98    4910 2130.64    4920 2129.57  4946.6 2123.25
  4951.6 2123.98  4960.2 2122.48  4988.2 2120.16  4988.5 2119.66  4992.3 2119.66
  4992.6 2120.16  4997.7 2121.36  5064.2 2125.43  5071.1 2126.84  5113.5 2128.36
  5134.9 2132.57    5156 2130.64    5229 2131.72  5311.7 2133.45    5336 2134.69
    5340 2135.29  5361.1 2135.17  5382.5 2136.63  5417.7 2137.54  5431.9 2138.33
  5439.1 2139.45  5501.1 2142.02  5530.9 2143.42  5545.1 2145.02  5580.5 2146.85
#Mann= 6 ,-1 , 0
  4799.4     .07       0  4988.2     .07       0  4992.6     .07       0
    5229    .035       0    5336     .07       0  5501.1    .035       0
Bank Sta=4988.2,4992.6
XS Rating Curve= 0 ,0
Exp/Cntr=0.3,0.1

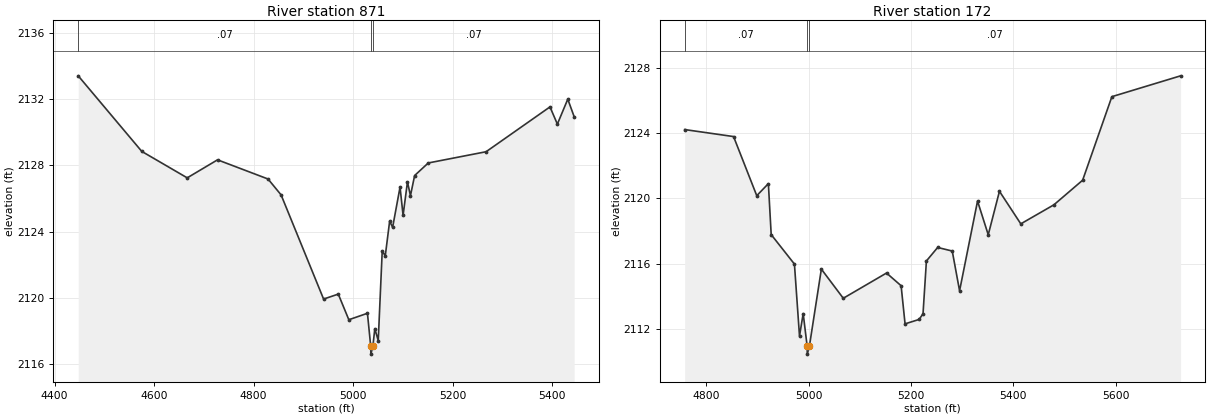
Type RM Length L Ch R = 1 ,871     ,699,699,699
BEGIN DESCRIPTION:
Sweetwater Creek Trib 27 T3_2 4033
END DESCRIPTION:
XS GIS Cut Line= 3
      1370750.89      6883242.05      1370206.45      6883148.64
      1369841.66      6883401.75
#Sta/Elev= 30
  4447.6 2133.42  4575.3 2128.85  4666.6 2127.25  4727.5 2128.34    4829 2127.18
  4855.2 2126.22  4940.6 2119.92  4970.1 2120.22  4991.3 2118.67  5028.7 2119.06
  5035.2 2117.09  5035.6 2116.59  5039.7 2117.09  5043.5 2118.13  5050.4 2117.41
  5058.4 2122.83  5064.5 2122.53  5073.3 2124.63  5079.3 2124.26  5094.2 2126.69
  5100.3 2124.98  5109.1 2127.01  5115.1 2126.17  5123.5 2127.39  5150.9 2128.15
  5267.1 2128.83  5395.4 2131.54  5410.3  2130.5  5431.2 2132.01    5444 2130.95
#Mann= 3 ,-1 , 0
  4447.6     .07       0  5035.2     .07       0  5039.7     .07       0
Bank Sta=5035.2,5039.7
XS Rating Curve= 0 ,0
Exp/Cntr=0.3,0.1

Type RM Length L Ch R = 1 ,172     ,0,0,0
BEGIN DESCRIPTION:
Sweetwater Creek Trib 27 T3_2 4393
END DESCRIPTION:
XS GIS Cut Line= 3
      1370737.31      6882582.27      1370519.17      6882686.82
      1369966.95       6883159.5
#Sta/Elev= 30
  4758.1 2124.23  4853.6  2123.8  4898.9 2120.17  4921.6 2120.91  4927.1 2117.78
  4972.5 2115.97  4982.4 2111.55  4989.6 2112.93  4997.3 2110.94  4997.6 2110.44
  5001.8 2110.94  5025.1 2115.66  5067.9 2113.87  5152.4 2115.42  5180.9 2114.64
  5188.6  2112.3  5216.1 2112.57  5223.7 2112.92  5230.3 2116.16  5252.3 2116.99
  5280.8 2116.77  5295.1 2114.33  5330.2 2119.84  5351.1 2117.77    5373 2120.44
  5414.7 2118.44  5479.4 2119.61  5535.5 2121.12  5592.6 2126.25  5726.9 2127.53
#Mann= 3 ,-1 , 0
  4758.1     .07       0  4997.3     .07       0  5001.8     .07       0
Bank Sta=4997.3,5001.8
XS Rating Curve= 0 ,0
Exp/Cntr=0.3,0.1

Chan Stop Cuts=-1
Use User Specified Reach Order=0
Composite Channel Slope=5