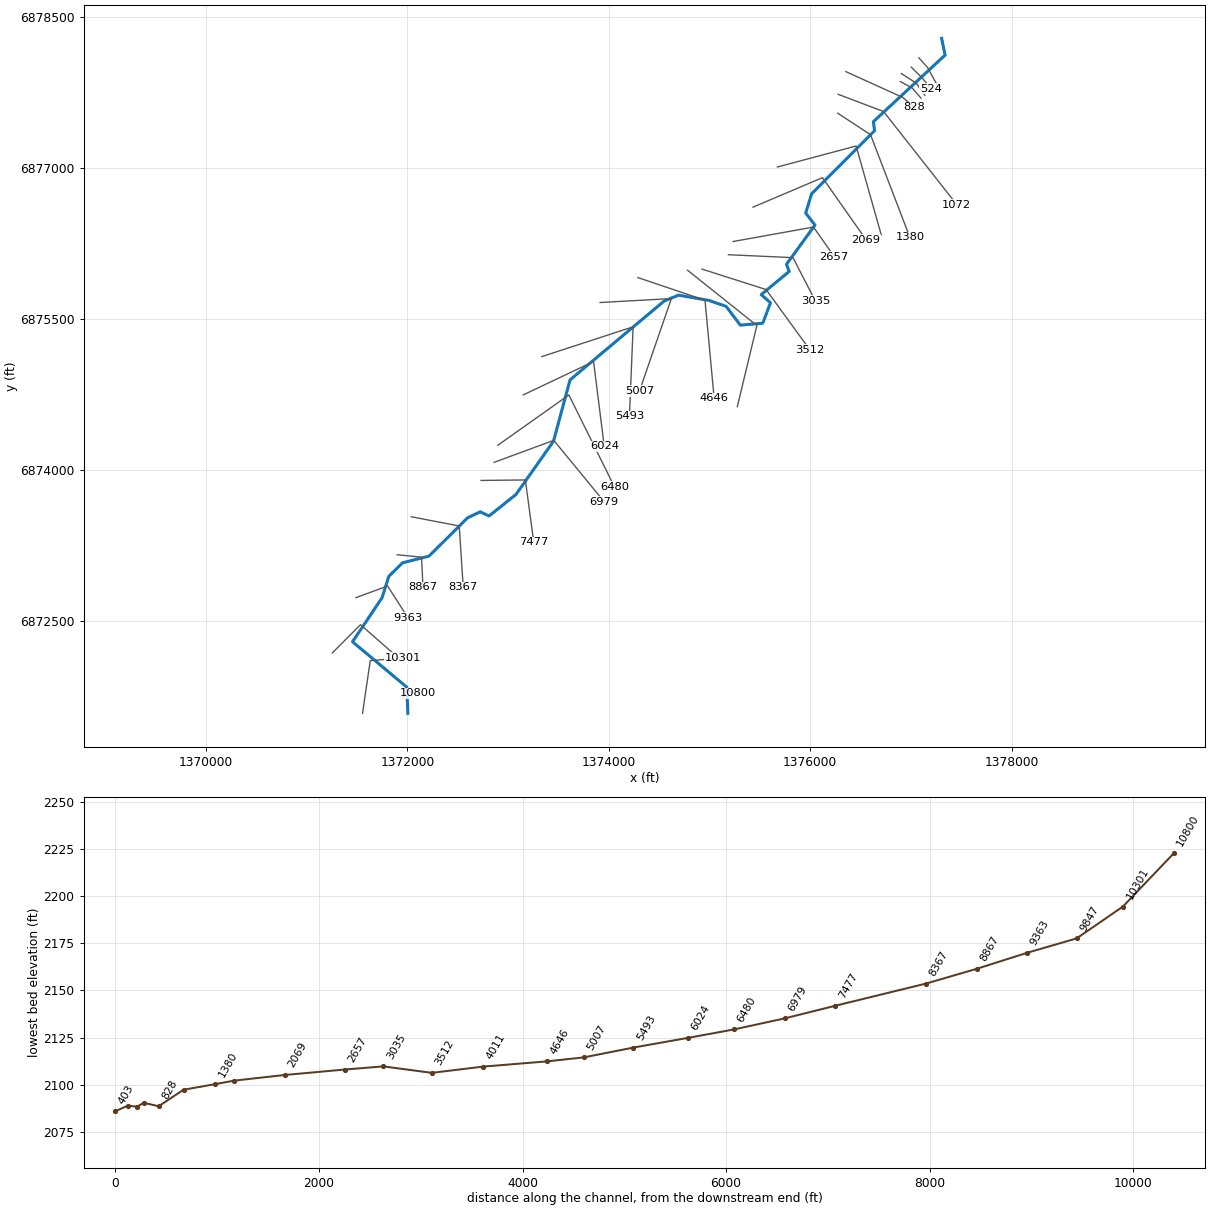
--- Sweetwater Creek Trib 27 T4.prj (project) ---

Proj Title=Sweetwater Creek Trib 27 T4 Base Level Engineering
Current Plan=p01
Default Exp/Contr=0.3,0.1
English Units
Geom File=g01
Flow File=f01
Plan File=p01
Y Axis Title=Elevation
X Axis Title(PF)=Main Channel Distance
X Axis Title(XS)=Station
BEGIN DESCRIPTION:
Sweetwater Creek Trib 27 T4
END DESCRIPTION:
DSS Export Rating Curves= 0
DSS Export Rating Curve Sorted= 0
DSS Export Volume Flow Curves= 0
DXF OffsetX= 0
DXF OffsetY= 0
DXF ScaleX= 1
DXF ScaleY= 10

--- Sweetwater Creek Trib 27 T4.p01 (plan) ---

Plan Title=Multiple Run
Short Identifier=Multiple
Geom File=g01
Flow File=f01
Subcritical Flow
K Sum by GR= 0
Std Step Tol= 0.01
Critical Tol= 0.01
Num of Std Step Trials= 20
Max Error Tol= 0.3
Flow Tol Ratio= 0.001
Split Flow NTrial= 30
Split Flow Tol= 0.02
Split Flow Ratio= 0.02
Log Output Level= 0
Friction Slope Method= 1
Unsteady Friction Slope Method= 2
Unsteady Bridges Friction Slope Method= 1
Parabolic Critical Depth
Global Vel Dist=  1 , 1 , 1
Global Log Level= 0
CheckData=True
Encroach Param= -1, 0, 0, 0
BEGIN DESCRIPTION:
Multiple Run
END DESCRIPTION:

--- Sweetwater Creek Trib 27 T4.f01 (steady flow) ---

Flow Title=Multiple
Program Version=4.10
Number of Profiles= 7
Profile Names=10-year,25-year,50-year,1pct_min,100-year,1pct_plu,500-year
River Rch & RM=Sweetwater Creek,Reach-1         ,10800
     233     327     405     249     498     993     763
Boundary for River Rch & Prof#=Sweetwater Creek,Reach-1         , 1
Up Type= 0
Dn Type= 3
Dn Slope=0.024
Boundary for River Rch & Prof#=Sweetwater Creek,Reach-1         , 2
Up Type= 0
Dn Type= 3
Dn Slope=0.024
Boundary for River Rch & Prof#=Sweetwater Creek,Reach-1         , 3
Up Type= 0
Dn Type= 3
Dn Slope=0.024
Boundary for River Rch & Prof#=Sweetwater Creek,Reach-1         , 4
Up Type= 0
Dn Type= 3
Dn Slope=0.024
Boundary for River Rch & Prof#=Sweetwater Creek,Reach-1         , 5
Up Type= 0
Dn Type= 3
Dn Slope=0.024
Boundary for River Rch & Prof#=Sweetwater Creek,Reach-1         , 6
Up Type= 0
Dn Type= 3
Dn Slope=0.024
Boundary for River Rch & Prof#=Sweetwater Creek,Reach-1         , 7
Up Type= 0
Dn Type= 3
Dn Slope=0.024
DSS Import GetInterval= 0
DSS Import GetPeak= 0
DSS Import FillOption= 0

--- Sweetwater Creek Trib 27 T4.g01 (geometry) ---

Geom Title=Existing Conditions
Program Version=4.10

River Reach=Sweetwater Creek,Reach-1
Reach XY= 30
        1372005.        6871588.      1371994.52       6871847.8
      1371455.59      6872298.62      1371749.17       6872735.7
      1371815.52      6872947.79      1371952.57      6873082.48
      1372214.79      6873148.52      1372598.94      6873529.86
      1372723.46      6873588.12      1372811.73      6873547.15
      1373078.84      6873760.86      1373451.38       6874289.5
      1373615.35      6874898.12      1374548.94      6875679.86
       1374691.3      6875738.74       1374994.5      6875686.78
      1375164.81      6875627.49      1375306.25      6875441.45
      1375528.91       6875460.7      1375605.51      6875663.12
      1375513.91      6875744.52      1375791.36      6875974.64
      1375764.32      6876044.66       1376047.4      6876434.66
      1375955.25      6876553.22      1376013.16      6876744.05
      1376638.61      6877371.33      1376627.52      6877461.34
      1377338.73      6878121.26        1377305.        6878288.

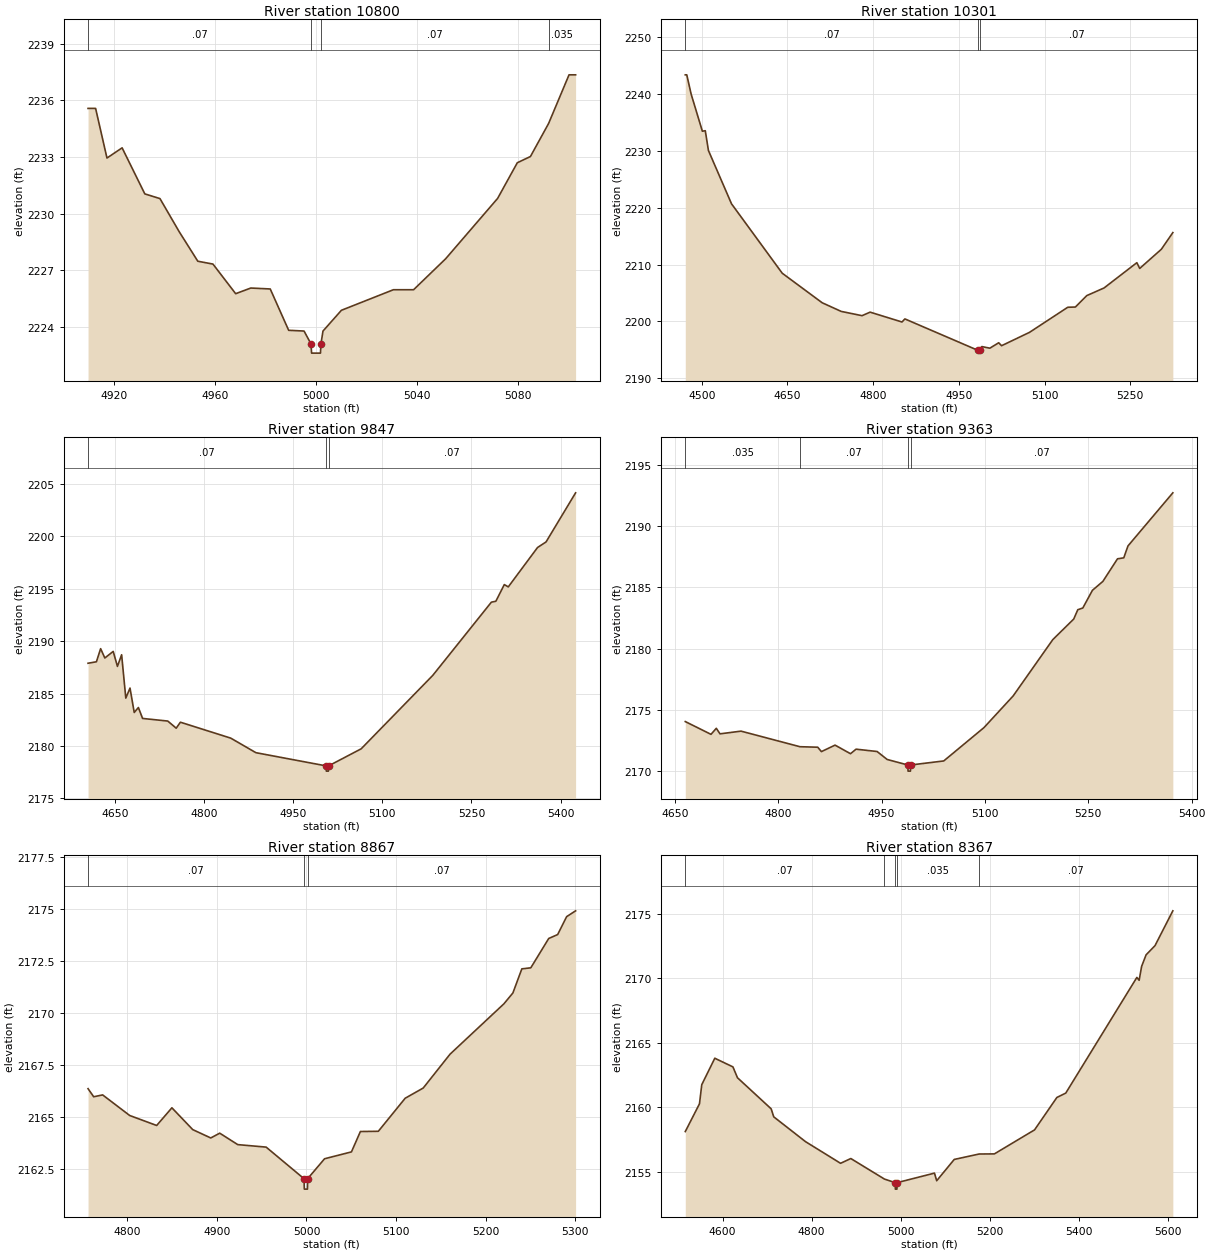
Type RM Length L Ch R = 1 ,10800   ,499,499,499
BEGIN DESCRIPTION:
Sweetwater Creek Trib 27 T4 19.0
END DESCRIPTION:
XS GIS Cut Line= 3
        1371955.      6871738.01       1372005.3      6871813.12
      1372104.98        6871788.
#Sta/Elev= 29
  4909.6 2235.57  4912.6 2235.57  4917.1 2232.94  4923.1 2233.48  4932.1 2231.04
  4938.1 2230.79  4945.7 2229.04  4953.1 2227.47  4959.1 2227.32  4968.1 2225.75
  4974.1 2226.05  4981.8    2226  4989.1 2223.81  4995.2 2223.77  4997.9  2223.1
  4998.2  2222.6  5001.7  2222.6  5001.9  2223.1  5002.7 2223.77    5010 2224.87
  5030.6 2225.96  5038.6 2225.96  5051.3  2227.6  5071.9  2230.8  5079.7 2232.69
  5084.9 2233.02  5092.1 2234.77  5100.2 2237.35  5102.8 2237.35
#Mann= 4 ,-1 , 0
  4909.6     .07       0  4997.9     .07       0  5001.9     .07       0
  5092.1    .035       0
Bank Sta=4997.9,5001.9
XS Rating Curve= 0 ,0
Exp/Cntr=0.3,0.1

Type RM Length L Ch R = 1 ,10301   ,454,454,454
BEGIN DESCRIPTION:
Sweetwater Creek Trib 27 T4 18.0
END DESCRIPTION:
XS GIS Cut Line= 3
      1371554.99      6871587.96      1371631.64      6872111.27
      1371955.04        6872138.
#Sta/Elev= 30
  4471.1 2243.34  4473.7 2243.34  4481.3 2239.97    4501 2233.43  4506.1 2233.52
  4511.6 2230.05    4552 2220.68  4640.8 2208.48  4710.7 2203.29    4744 2201.77
  4780.5 2201.02  4794.6 2201.64  4850.4 2199.91  4855.5 2200.45  4983.1 2194.94
  4983.4 2194.44  4987.1 2194.94  4990.2 2195.59  5004.2 2195.31  5019.7 2196.26
  5024.7 2195.74  5073.6 2198.09  5140.6  2202.5  5153.9 2202.54  5173.9 2204.55
  5204.1 2205.89  5261.5 2210.33  5266.5 2209.32  5304.4 2212.69  5324.5 2215.62
#Mann= 3 ,-1 , 0
  4471.1     .07       0  4983.1     .07       0  4987.1     .07       0
Bank Sta=4983.1,4987.1
XS Rating Curve= 0 ,0
Exp/Cntr=0.3,0.1

Type RM Length L Ch R = 1 ,9847    ,484,484,484
BEGIN DESCRIPTION:
Sweetwater Creek Trib 27 T4 17.0
END DESCRIPTION:
XS GIS Cut Line= 3
        1371255.        6872188.      1371534.82      6872468.07
      1371855.01      6872187.99
#Sta/Elev= 30
  4604.1 2187.89  4618.2 2188.03  4625.3 2189.28  4632.4 2188.39  4646.5 2189.02
  4653.6 2187.59  4660.7  2188.7  4667.7 2184.56  4674.8 2185.52  4681.9 2183.19
  4688.9 2183.66    4696 2182.62  4738.4 2182.37  4752.6 2181.69  4759.7 2182.26
  4844.5 2180.74  4886.9 2179.35  5005.3 2178.09  5005.5 2177.59    5009 2177.59
  5009.3 2178.09  5064.2 2179.72  5184.8 2186.73  5283.5 2193.72  5291.1 2193.81
  5305.3  2195.4    5312 2195.18  5361.3 2198.94  5375.6 2199.47  5425.4 2204.16
#Mann= 3 ,-1 , 0
  4604.1     .07       0  5005.3     .07       0  5009.3     .07       0
Bank Sta=5005.3,5009.3
XS Rating Curve= 0 ,0
Exp/Cntr=0.3,0.1

Type RM Length L Ch R = 1 ,9363    ,496,496,496
BEGIN DESCRIPTION:
Sweetwater Creek Trib 27 T4 16.0
END DESCRIPTION:
XS GIS Cut Line= 3
      1371489.99      6872736.64       1371804.2      6872851.97
        1372005.      6872537.99
#Sta/Elev= 30
  4665.3 2174.05  4702.6 2173.01  4710.3  2173.5  4715.7 2173.05  4746.2 2173.27
  4831.7    2172  4857.5 2171.96  4862.8  2171.6  4882.6 2172.13    4905 2171.43
  4913.1  2171.8  4943.6 2171.61  4958.2 2170.96  4988.2 2170.51  4988.5 2170.01
    4992 2170.01  4992.2 2170.51  5040.3 2170.84  5098.7 2173.56    5141 2176.14
  5198.5 2180.73  5228.9 2182.41  5234.8 2183.17  5242.1 2183.31    5256 2184.75
  5271.2 2185.48  5292.4 2187.32  5301.5  2187.4  5307.6 2188.37  5372.7  2192.7
#Mann= 4 ,-1 , 0
  4665.3    .035       0  4831.7     .07       0  4988.2     .07       0
  4992.2     .07       0
Bank Sta=4988.2,4992.2
XS Rating Curve= 0 ,0
Exp/Cntr=0.3,0.1

Type RM Length L Ch R = 1 ,8867    ,500,500,500
BEGIN DESCRIPTION:
Sweetwater Creek Trib 27 T4 15.0
END DESCRIPTION:
XS GIS Cut Line= 3
      1371898.74      6873162.59      1372141.31      6873138.13
        1372155.      6872838.04
#Sta/Elev= 30
  4756.2 2166.34  4762.5 2165.95  4772.5 2166.04  4802.7 2165.05  4832.8 2164.57
  4849.8 2165.42  4873.1 2164.37  4893.2 2163.97  4903.2  2164.2  4923.3 2163.65
    4955 2163.53  4997.3 2162.01  4997.6 2161.51  5001.1 2161.51  5001.3 2162.01
  5020.2 2162.97  5050.2  2163.3  5060.2 2164.28  5080.2 2164.29  5110.2 2165.88
  5130.3 2166.37  5160.3    2168  5220.4 2170.42  5230.4 2170.94  5240.4  2172.1
  5250.4 2172.15  5270.4 2173.56  5280.4 2173.75  5290.4 2174.61  5300.4 2174.89
#Mann= 3 ,-1 , 0
  4756.2     .07       0  4997.3     .07       0  5001.3     .07       0
Bank Sta=4997.3,5001.3
XS Rating Curve= 0 ,0
Exp/Cntr=0.3,0.1

Type RM Length L Ch R = 1 ,8367    ,890,890,890
BEGIN DESCRIPTION:
Sweetwater Creek Trib 27 T4 14.0
END DESCRIPTION:
XS GIS Cut Line= 3
      1372039.87      6873539.26      1372514.99      6873448.02
        1372555.      6872838.03
#Sta/Elev= 30
  4516.2 2158.13  4548.1 2160.28  4553.2 2161.76  4582.5 2163.81  4623.2 2163.14
  4633.4  2162.3  4709.1 2159.89  4714.9 2159.27  4786.2 2157.35    4865 2155.67
    4888 2156.04  4963.5 2154.45  4987.8 2154.17  4988.1 2153.67  4991.6 2153.67
  4991.8 2154.17  5075.9 2154.91  5080.9 2154.32  5120.3 2155.97  5176.2 2156.39
  5210.5  2156.4  5300.7 2158.26  5350.8 2160.77  5370.8 2161.11  5530.5 2170.07
  5535.6 2169.85  5541.2 2170.93  5551.2 2171.82  5571.2 2172.53  5611.3 2175.23
#Mann= 5 ,-1 , 0
  4516.2     .07       0  4963.5    .035       0  4987.8    .035       0
  4991.8    .035       0  5176.2     .07       0
Bank Sta=4987.8,4991.8
XS Rating Curve= 0 ,0
Exp/Cntr=0.3,0.1

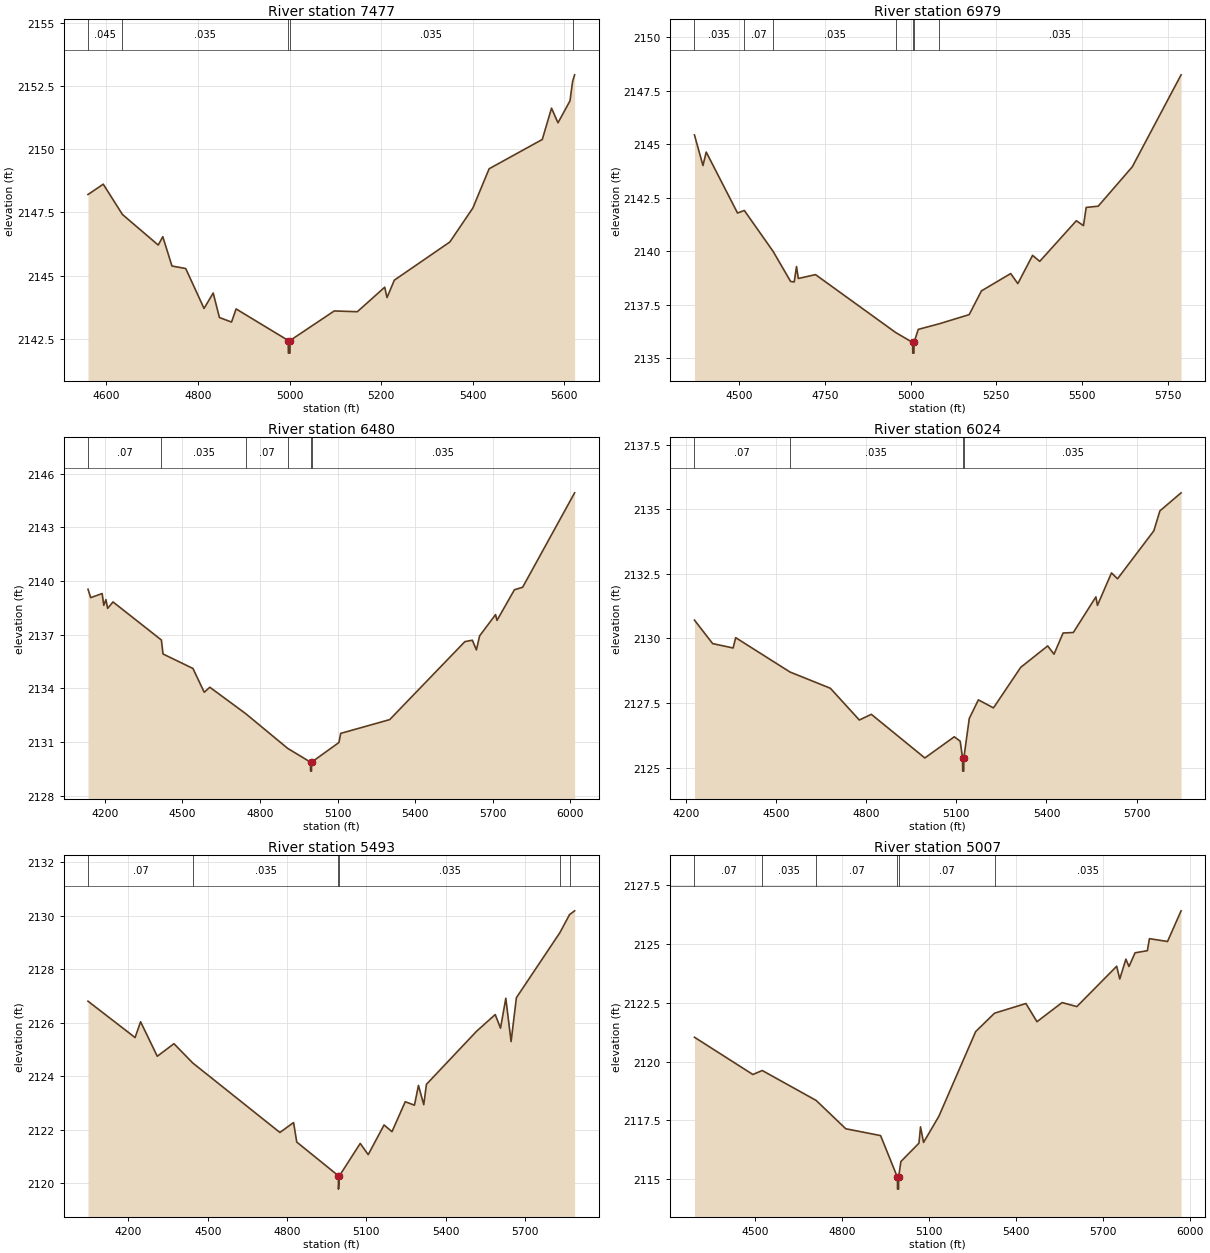
Type RM Length L Ch R = 1 ,7477    ,498,498,498
BEGIN DESCRIPTION:
Sweetwater Creek Trib 27 T4 13.0
END DESCRIPTION:
XS GIS Cut Line= 3
      1372731.71      6873899.85      1373171.58       6873904.7
        1373255.      6873288.02
#Sta/Elev= 30
  4560.1 2148.21  4593.4 2148.62  4635.3 2147.42  4713.4 2146.21  4723.4 2146.54
  4743.4 2145.38  4773.4 2145.28  4813.4  2143.7  4833.4 2144.31    4847 2143.34
  4873.4 2143.16  4883.4 2143.68  4997.2 2142.43  4997.5 2141.93    5001 2141.93
  5001.2 2142.43  5097.6  2143.6    5148 2143.57  5207.8 2144.54  5212.8 2144.13
  5228.8 2144.82  5349.9 2146.33  5400.3 2147.68  5435.7 2149.23  5551.7 2150.39
  5571.9 2151.63    5586 2151.05  5612.2 2151.92  5617.8 2152.68  5622.3 2152.95
#Mann= 5 ,-1 , 0
  4560.1    .045       0  4635.3    .035       0  4997.2    .035       0
  5001.2    .035       0  5617.8     .07       0
Bank Sta=4997.2,5001.2
XS Rating Curve= 0 ,0
Exp/Cntr=0.3,0.1

Type RM Length L Ch R = 1 ,6979    ,499,499,499
BEGIN DESCRIPTION:
Sweetwater Creek Trib 27 T4 12.0
END DESCRIPTION:
XS GIS Cut Line= 3
      1372861.72       6874079.7      1373453.68      6874297.64
      1373955.01      6873687.99
#Sta/Elev= 30
  4369.2 2145.43    4394    2144  4403.5 2144.63  4494.9 2141.78  4514.7  2141.9
    4599 2139.98  4649.8 2138.58  4660.4 2138.56    4667 2139.28  4672.3 2138.72
  4722.5  2138.9  4956.7 2136.19    5006 2135.73  5006.2 2135.23  5009.7 2135.23
    5010 2135.73  5022.3 2136.34  5083.1  2136.6  5170.9 2137.03  5206.7 2138.14
  5292.1 2138.95  5312.9 2138.48  5355.9  2139.8  5376.8 2139.52  5483.7 2141.42
  5504.5 2141.19  5512.3 2142.04  5547.5  2142.1  5646.9 2143.94  5789.3 2148.24
#Mann= 7 ,-1 , 0
  4369.2    .035       0  4514.7     .07       0    4599    .035       0
  4956.7     .07       0    5006     .07       0    5010     .07       0
  5083.1    .035       0
Bank Sta=5006,5010
XS Rating Curve= 0 ,0
Exp/Cntr=0.3,0.1

Type RM Length L Ch R = 1 ,6480    ,456,456,456
BEGIN DESCRIPTION:
Sweetwater Creek Trib 27 T4 11.0
END DESCRIPTION:
XS GIS Cut Line= 3
      1372898.37      6874249.09      1373603.77      6874748.51
      1374055.01      6873837.99
#Sta/Elev= 30
  4135.7 2139.54  4146.2 2139.07  4190.5  2139.3  4196.7 2138.64  4205.1 2138.96
  4211.5 2138.47  4232.4 2138.83  4419.4  2136.7  4425.6 2135.92  4541.3 2135.11
  4584.9 2133.78  4606.5 2134.06  4744.6 2132.59  4907.7 2130.64  4995.7 2129.87
  4995.9 2129.37  4999.4 2129.37  4999.7 2129.87  5105.4 2130.97  5112.2 2131.48
  5301.6 2132.25  5592.1 2136.61    5621 2136.69  5636.7 2136.15    5649 2136.93
  5710.7 2138.12  5716.3  2137.8  5783.6 2139.51  5815.3 2139.65  6016.2 2144.93
#Mann= 6 ,-1 , 0
  4135.7     .07       0  4419.4    .035       0  4744.6     .07       0
  4907.7    .035       0  4995.7    .035       0  4999.7    .035       0
Bank Sta=4995.7,4999.7
XS Rating Curve= 0 ,0
Exp/Cntr=0.3,0.1

Type RM Length L Ch R = 1 ,6024    ,531,531,531
BEGIN DESCRIPTION:
Sweetwater Creek Trib 27 T4 10.0
END DESCRIPTION:
XS GIS Cut Line= 3
      1373150.95      6874749.08      1373848.95      6875079.84
        1373955.      6874237.99
#Sta/Elev= 30
  4227.6 2130.71  4288.2  2129.8  4356.4 2129.63  4364.9 2130.03  4545.7  2128.7
  4680.3 2128.07  4776.8 2126.84  4816.8 2127.06    4995 2125.37    5093 2126.19
  5112.7 2126.02  5120.8 2125.36  5121.1 2124.86  5124.6 2124.86  5124.8 2125.36
    5143  2126.9  5173.3 2127.62  5223.6 2127.31  5314.3 2128.88  5404.2 2129.71
  5425.2 2129.39  5455.4 2130.21  5489.6 2130.23  5564.8 2131.61  5569.9 2131.28
  5616.7 2132.54  5636.8 2132.31  5757.8 2134.17  5777.9 2134.94  5848.5 2135.64
#Mann= 4 ,-1 , 0
  4227.6     .07       0  4545.7    .035       0  5120.8    .035       0
  5124.8    .035       0
Bank Sta=5120.8,5124.8
XS Rating Curve= 0 ,0
Exp/Cntr=0.3,0.1

Type RM Length L Ch R = 1 ,5493    ,486,486,486
BEGIN DESCRIPTION:
Sweetwater Creek Trib 27 T4 9.0
END DESCRIPTION:
XS GIS Cut Line= 3
       1373335.9      6875129.31      1374241.62      6875424.77
        1374205.      6874538.03
#Sta/Elev= 30
  4047.3 2126.81  4225.4 2125.45  4246.2 2126.04  4309.3 2124.75  4372.4 2125.22
  4443.3  2124.5    4773  2121.9  4824.7 2122.27  4836.8 2121.54  4994.3 2120.28
  4994.5 2119.78  4998.3 2120.28  5076.8 2121.49  5106.9 2121.07  5166.9 2122.18
  5196.9 2121.93    5247 2123.05  5281.8 2122.92    5297 2123.66    5317 2122.94
  5327.1  2123.7  5517.2 2125.69  5587.3 2126.31  5607.3  2125.8  5627.3 2126.92
  5647.3  2125.3  5667.3 2126.94  5831.6 2129.37  5868.4 2130.05  5887.5 2130.19
#Mann= 6 ,-1 , 0
  4047.3     .07       0  4443.3    .035       0  4994.3    .035       0
  4998.3    .035       0  5831.6     .07       0  5868.4    .035       0
Bank Sta=4994.3,4998.3
XS Rating Curve= 0 ,0
Exp/Cntr=0.3,0.1

Type RM Length L Ch R = 1 ,5007    ,361,361,361
BEGIN DESCRIPTION:
Sweetwater Creek Trib 27 T4 8.0
END DESCRIPTION:
XS GIS Cut Line= 3
      1373913.67      6875665.84      1374621.48      6875705.12
        1374305.        6874788.
#Sta/Elev= 30
  4291.1 2121.03  4492.7 2119.45    4525 2119.62  4711.1 2118.35  4813.2 2117.15
  4933.4 2116.86  4991.5 2115.09  4991.8 2114.59  4995.3 2114.59  4995.5 2115.09
  5003.4 2115.76  5065.8 2116.54  5071.1 2117.23  5081.6 2116.57  5134.5 2117.68
  5261.4 2121.27  5326.5 2122.05  5434.8 2122.46    5473 2121.69  5559.6  2122.5
  5610.5 2122.33    5748 2124.04  5758.6  2123.5  5779.8 2124.34  5790.4 2124.03
  5811.5 2124.61  5853.8  2124.7    5861 2125.21  5923.4 2125.09  5970.2 2126.39
#Mann= 6 ,-1 , 0
  4291.1     .07       0    4525    .035       0  4711.1     .07       0
  4991.5     .07       0  4995.5     .07       0  5326.5    .035       0
Bank Sta=4991.5,4995.5
XS Rating Curve= 0 ,0
Exp/Cntr=0.3,0.1

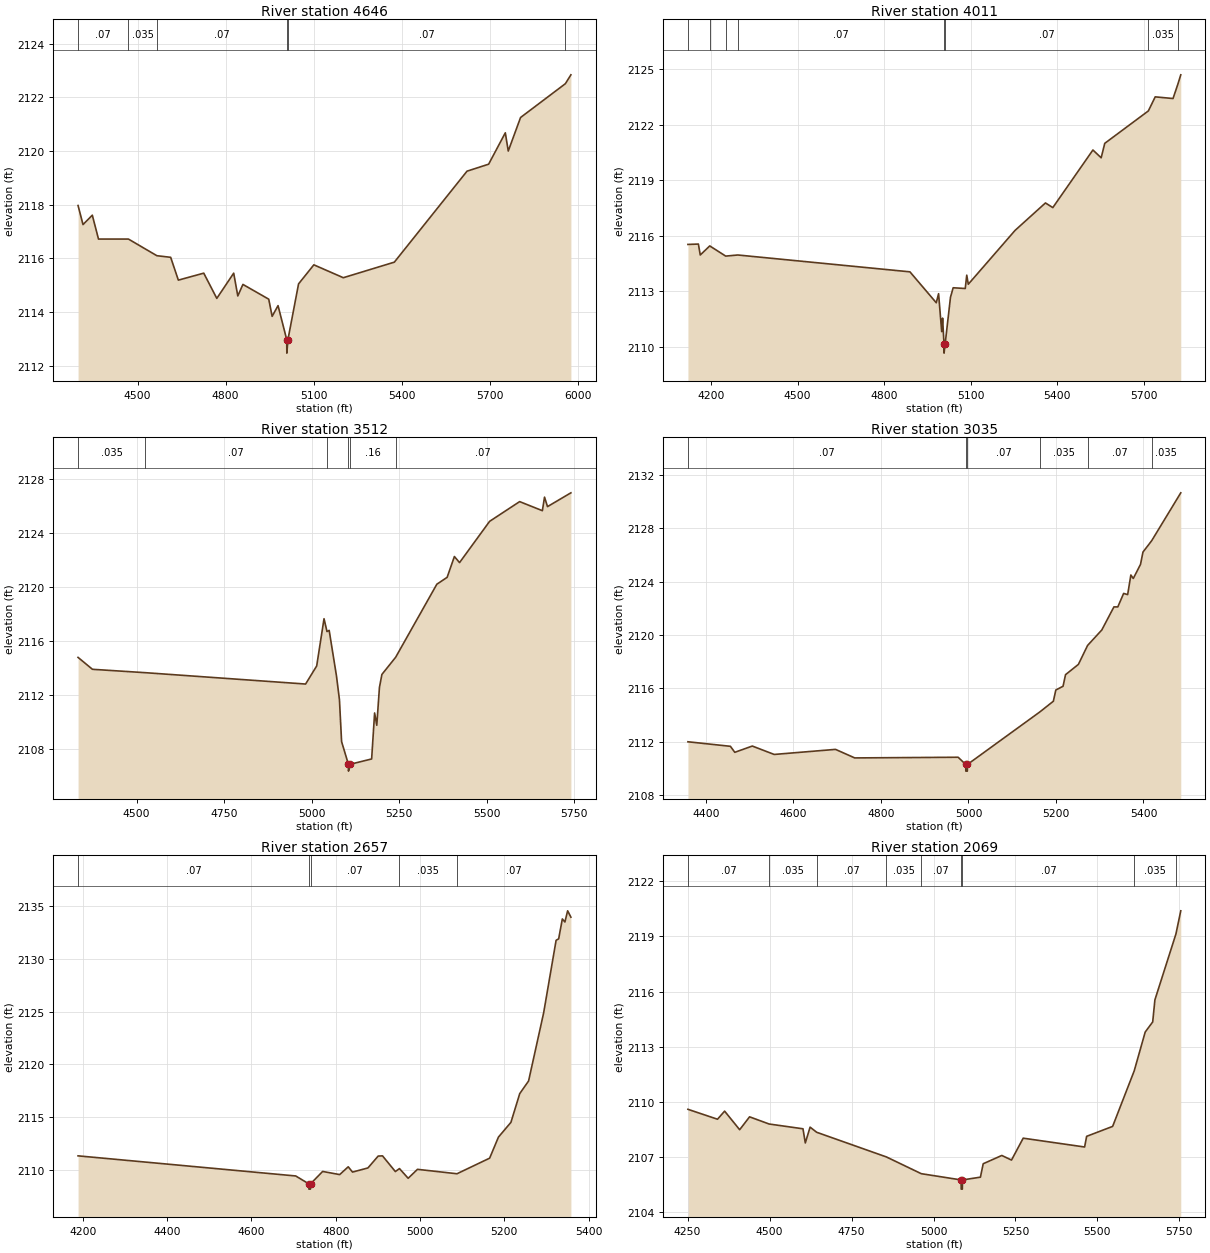
Type RM Length L Ch R = 1 ,4646    ,635,635,635
BEGIN DESCRIPTION:
Sweetwater Creek Trib 27 T4 4209
END DESCRIPTION:
XS GIS Cut Line= 3
      1374288.94      6875913.43      1374955.17       6875688.4
      1375046.31      6874715.36
#Sta/Elev= 30
  4296.8 2117.97  4313.7 2117.26  4345.4 2117.61  4366.5 2116.72  4468.6 2116.72
  4565.6  2116.1  4612.6 2116.04  4638.8 2115.19  4725.4 2115.45  4769.9 2114.51
  4827.5 2115.45  4841.5  2114.6    4859 2115.03    4947 2114.48  4958.6 2113.84
  4978.7 2114.24  5008.4 2112.97  5008.7 2112.47  5012.4 2112.97  5048.7 2115.05
  5100.8 2115.76  5201.3 2115.28  5375.3 2115.86  5623.1 2119.25  5696.8 2119.51
  5753.7 2120.68  5763.7    2120  5805.7 2121.25  5958.5 2122.51  5977.3 2122.84
#Mann= 6 ,-1 , 0
  4296.8     .07       0  4468.6    .035       0  4565.6     .07       0
  5008.4     .07       0  5012.4     .07       0  5958.5    .035       0
Bank Sta=5008.4,5012.4
XS Rating Curve= 0 ,0
Exp/Cntr=0.3,0.1

Type RM Length L Ch R = 1 ,4011    ,499,499,499
BEGIN DESCRIPTION:
Sweetwater Creek Trib 27 T4 7.0
END DESCRIPTION:
XS GIS Cut Line= 3
      1374782.23      6875986.13      1375470.26      6875437.48
      1375275.98      6874631.88
#Sta/Elev= 30
    4120 2115.53  4156.3 2115.55  4162.7 2114.96  4195.7 2115.45  4250.9  2114.9
  4292.9 2114.96  4889.7 2114.05    4981 2112.38    4989 2112.87  4999.8 2110.82
  5002.9 2111.55  5007.8 2110.16    5008 2109.66  5011.8 2110.16  5030.3 2112.68
  5039.6 2113.19  5081.5 2113.15  5086.7 2113.87    5092 2113.38  5254.3 2116.29
  5359.5 2117.77  5385.1 2117.52  5524.1 2120.63  5552.7 2120.21  5565.2 2120.99
  5716.3 2122.74  5740.1  2123.5  5801.8 2123.41  5817.7 2124.14  5828.7 2124.69
#Mann= 8 ,-1 , 0
    4120    .035       0  4195.7     .07       0  4250.9    .035       0
  4292.9     .07       0  5007.8     .07       0  5011.8     .07       0
  5716.3    .035       0  5817.7     .07       0
Bank Sta=5007.8,5011.8
XS Rating Curve= 0 ,0
Exp/Cntr=0.3,0.1

Type RM Length L Ch R = 1 ,3512    ,477,477,477
BEGIN DESCRIPTION:
Sweetwater Creek Trib 27 T4 6.0
END DESCRIPTION:
XS GIS Cut Line= 3
      1374925.88      6875997.47      1375561.31      6875794.68
      1375997.06      6875195.84
#Sta/Elev= 30
    4333 2114.79  4374.1 2113.91  4524.9 2113.66  4982.9 2112.82  5014.6 2114.16
  5035.5 2117.65    5044  2116.7  5050.2 2116.79    5071 2113.43  5079.5 2111.68
  5085.7 2108.56  5105.2 2106.88  5105.4 2106.38  5109.2 2106.88  5171.5 2107.28
    5180 2110.68  5186.2 2109.77  5193.8 2112.57  5200.8 2113.53  5240.1  2114.8
  5357.7  2120.2  5387.1 2120.71  5407.9 2122.25  5422.6  2121.8  5508.4 2124.85
  5594.2 2126.31  5659.1 2125.64  5665.3 2126.64  5673.8 2125.94  5740.6 2126.96
#Mann= 6 ,-1 , 0
    4333    .035       0  4524.9     .07       0    5044     .16       0
  5105.2     .07       0  5109.2     .16       0  5240.1     .07       0
Bank Sta=5105.2,5109.2
XS Rating Curve= 0 ,0
Exp/Cntr=0.3,0.1

Type RM Length L Ch R = 1 ,3035    ,378,378,378
BEGIN DESCRIPTION:
Sweetwater Creek Trib 27 T4 5.0
END DESCRIPTION:
XS GIS Cut Line= 3
      1375188.04      6876140.24      1375828.58      6876111.18
      1376051.74      6875680.23
#Sta/Elev= 30
  4358.8    2112  4455.9 2111.66  4465.9 2111.21  4505.9 2111.68    4556 2111.05
  4696.1 2111.43  4740.1 2110.79  4976.4 2110.84  4993.7  2110.3    4994  2109.8
  4997.5  2109.8  4997.7  2110.3  5163.3 2114.24  5194.1 2115.04  5199.7 2115.88
  5216.2 2116.16  5221.9 2117.03  5251.3  2117.8  5272.3 2119.22  5304.8 2120.38
  5332.5 2122.11  5341.4 2122.11  5354.7 2123.12  5363.9 2123.03  5371.2  2124.5
  5376.8 2124.24  5393.3  2125.3  5398.9 2126.22  5418.8 2127.07  5485.3 2130.66
#Mann= 6 ,-1 , 0
  4358.8     .07       0  4993.7     .07       0  4997.7     .07       0
  5163.3    .035       0  5272.3     .07       0  5418.8    .035       0
Bank Sta=4993.7,4997.7
XS Rating Curve= 0 ,0
Exp/Cntr=0.3,0.1

Type RM Length L Ch R = 1 ,2657    ,588,588,588
BEGIN DESCRIPTION:
Sweetwater Creek Trib 27 T4 4.0
END DESCRIPTION:
XS GIS Cut Line= 3
      1375234.07      6876271.36      1376032.61      6876414.67
      1376238.31      6876121.66
#Sta/Elev= 30
  4188.7  2111.3  4705.1 2109.39  4736.3 2108.64  4736.5 2108.14    4740 2108.14
  4740.3 2108.64    4769 2109.82  4809.4 2109.52  4829.7 2110.26  4839.9 2109.76
  4876.4 2110.15  4900.8 2111.28    4911  2111.3  4941.5 2109.81  4951.3 2110.09
  4971.9 2109.17    4994 2110.02  5087.7  2109.6  5165.2 2111.08  5186.1 2113.08
  5215.7 2114.48  5236.6 2117.21  5257.6 2118.41  5293.3 2124.87  5322.9 2131.77
    5329 2131.91  5337.7  2133.8  5343.8 2133.51  5350.3 2134.57    5358 2133.97
#Mann= 5 ,-1 , 0
  4188.7     .07       0  4736.3    .035       0  4740.3     .07       0
  4951.3    .035       0  5087.7     .07       0
Bank Sta=4736.3,4740.3
XS Rating Curve= 0 ,0
Exp/Cntr=0.3,0.1

Type RM Length L Ch R = 1 ,2069    ,500,500,500
BEGIN DESCRIPTION:
Sweetwater Creek Trib 27 T4 3.0
END DESCRIPTION:
XS GIS Cut Line= 3
      1375431.99      6876612.51      1376121.46      6876905.13
      1376555.01      6876287.99
#Sta/Elev= 30
    4251  2109.6  4341.2 2109.06  4362.9  2109.5  4408.8 2108.49    4439 2109.19
  4498.7  2108.8  4601.9 2108.54    4609 2107.77  4623.6 2108.63  4643.8 2108.35
  4856.3 2107.01  4962.6  2106.1  5084.3 2105.76  5084.5 2105.26    5088 2105.26
  5088.3 2105.76  5143.1 2105.91  5151.6 2106.64  5208.3 2107.09  5237.9 2106.84
  5273.6 2108.03  5460.9 2107.55  5467.1 2108.13  5546.4 2108.67  5612.2 2111.69
  5645.7  2113.8  5668.6 2114.35  5675.3 2115.55  5739.4 2119.13  5754.2 2120.39
#Mann= 9 ,-1 , 0
    4251     .07       0  4498.7    .035       0  4643.8     .07       0
  4856.3    .035       0  4962.6     .07       0  5084.3     .07       0
  5088.3     .07       0  5612.2    .035       0  5739.4     .07       0
Bank Sta=5084.3,5088.3
XS Rating Curve= 0 ,0
Exp/Cntr=0.3,0.1

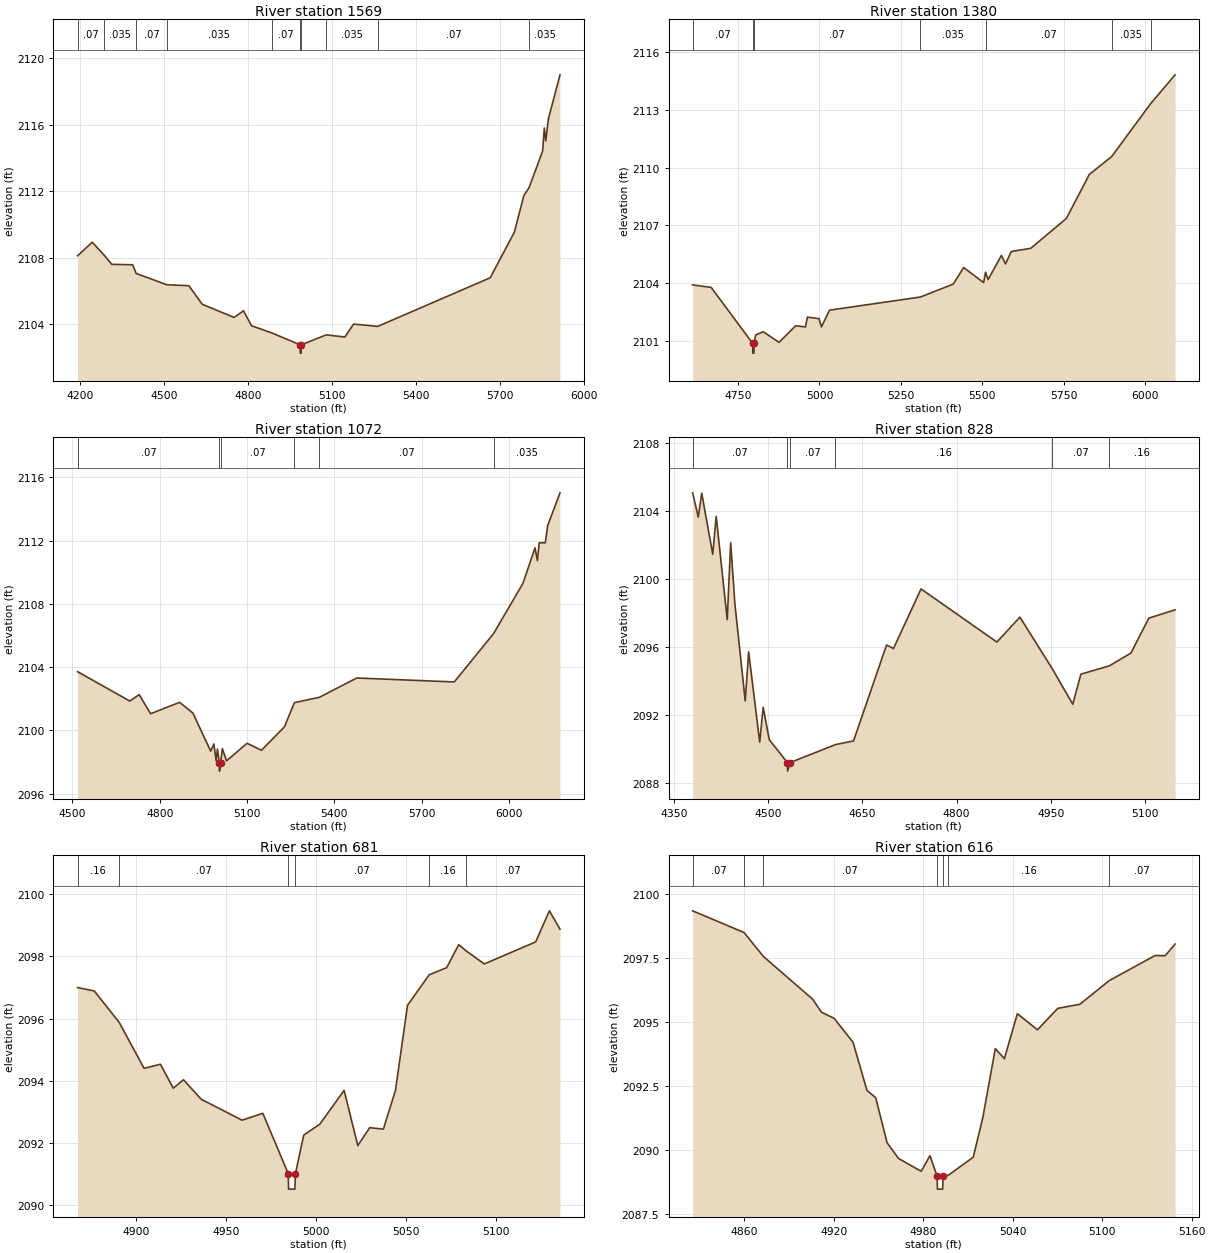
Type RM Length L Ch R = 1 ,1569    ,189,189,189
BEGIN DESCRIPTION:
Sweetwater Creek Trib 27 T4 2.0
END DESCRIPTION:
XS GIS Cut Line= 3
      1375674.18      6877010.95       1376455.7      6877219.24
      1376704.99      6876338.02
#Sta/Elev= 30
  4191.2 2108.11  4243.8 2108.93  4286.9 2108.14  4313.4  2107.6  4388.4 2107.57
  4400.6 2107.05    4510 2106.37    4589 2106.31  4637.1 2105.19  4750.9  2104.4
  4784.4  2104.8    4813  2103.9  4886.7 2103.46  4986.9 2102.75  4987.2 2102.25
  4990.7 2102.25  4990.9 2102.75  5080.3 2103.35  5146.8 2103.22    5178    2104
  5264.3 2103.86  5666.4 2106.79  5752.6 2109.53  5786.6 2111.74    5805 2112.21
  5853.5 2114.41  5859.7 2115.81  5864.9 2115.03  5874.3 2116.36  5915.8 2119.01
#Mann= 10 ,-1 , 0
  4191.2     .07       0  4286.9    .035       0  4400.6     .07       0
    4510    .035       0  4886.7     .07       0  4986.9     .07       0
  4990.9     .07       0  5080.3    .035       0  5264.3     .07       0
    5805    .035       0
Bank Sta=4986.9,4990.9
XS Rating Curve= 0 ,0
Exp/Cntr=0.3,0.1

Type RM Length L Ch R = 1 ,1380    ,308,308,308
BEGIN DESCRIPTION:
Sweetwater Creek Trib 27 T4 4210
END DESCRIPTION:
XS GIS Cut Line= 3
      1376273.28      6877544.85      1376598.67      6877331.32
      1376989.71      6876312.16
#Sta/Elev= 30
  4610.8 2103.91  4667.8 2103.78  4795.3 2100.87  4795.6 2100.37  4799.1 2100.37
  4799.3 2100.87  4804.2 2101.31  4827.5 2101.48    4876 2100.93  4926.9 2101.79
  4957.1 2101.73  4963.1 2102.24  4998.5 2102.16  5006.3 2101.73    5031  2102.6
  5309.9 2103.28  5410.6 2103.95  5442.7 2104.81  5503.9 2104.03  5509.8 2104.57
  5517.7 2104.19  5558.6 2105.44  5571.2    2105  5588.6 2105.64  5648.7 2105.81
    5758 2107.36  5828.3 2109.64    5897 2110.57  6016.8 2113.32  6091.6 2114.81
#Mann= 7 ,-1 , 0
  4610.8     .07       0  4795.3     .07       0  4799.3     .07       0
  5309.9    .035       0  5509.8     .07       0    5897    .035       0
  6016.8     .07       0
Bank Sta=4795.3,4799.3
XS Rating Curve= 0 ,0
Exp/Cntr=0.3,0.1

Type RM Length L Ch R = 1 ,1072    ,244,244,244
BEGIN DESCRIPTION:
Sweetwater Creek Trib 27 T4 1.0
END DESCRIPTION:
XS GIS Cut Line= 3
      1376276.89      6877732.44      1376728.18       6877561.7
      1377455.02      6876637.98
#Sta/Elev= 30
  4517.5 2103.72  4697.2 2101.86  4729.3 2102.27  4768.5 2101.06  4868.3 2101.78
    4914  2101.1  4975.2 2098.69  4985.9 2099.15  4993.8 2098.09  4998.2 2098.82
    5005 2097.93  5005.3 2097.43    5009 2097.93  5015.1 2098.85  5029.5 2098.08
  5100.1 2099.19  5149.8 2098.75  5228.4 2100.23  5262.8 2101.76  5348.7  2102.1
  5476.9 2103.32  5812.1 2103.07  5947.2 2106.13  6047.9  2109.3  6089.5 2111.55
  6097.6 2110.74    6104 2111.87  6124.8 2111.87  6132.9 2112.95  6175.4 2115.03
#Mann= 6 ,-1 , 0
  4517.5     .07       0    5005     .07       0    5009     .07       0
  5262.8     .16       0  5348.7     .07       0  5947.2    .035       0
Bank Sta=5005,5009
XS Rating Curve= 0 ,0
Exp/Cntr=0.3,0.1

Type RM Length L Ch R = 1 ,828     ,147,147,147
BEGIN DESCRIPTION:
Sweetwater Creek Trib 27 T4 4011
END DESCRIPTION:
XS GIS Cut Line= 3
      1376353.81       6877957.6      1376918.66      6877701.25
      1377031.45      6877605.58
#Sta/Elev= 30
  4379.7 2105.08  4388.7 2103.65  4394.2 2105.06  4411.7 2101.46  4417.2  2103.7
  4434.8 2097.61  4440.3 2102.14  4446.9 2098.58  4463.4 2092.83  4468.9 2095.71
  4486.5  2090.4    4492 2092.45  4501.8 2090.54  4530.6 2089.19  4530.9 2088.69
  4534.6 2089.19    4607 2090.25  4635.9 2090.47  4688.5 2096.12  4699.5 2095.91
  4743.4 2099.42  4864.2 2096.29  4900.8 2097.76    4952 2094.74    4985 2092.63
  4997.9  2094.4  5043.2 2094.89  5077.5 2095.64  5106.1  2097.7  5147.9 2098.19
#Mann= 6 ,-1 , 0
  4379.7     .07       0  4530.6     .07       0  4534.6     .07       0
    4607     .16       0    4952     .07       0  5043.2     .16       0
Bank Sta=4530.6,4534.6
XS Rating Curve= 0 ,0
Exp/Cntr=0.3,0.1

Type RM Length L Ch R = 1 ,681     ,65,65,65
BEGIN DESCRIPTION:
Sweetwater Creek Trib 27 T4 4010
END DESCRIPTION:
XS GIS Cut Line= 3
      1376894.48      6877858.85      1377011.02      6877796.21
      1377100.25      6877694.38
#Sta/Elev= 30
  4867.7    2097    4877 2096.89  4890.8 2095.88  4904.6  2094.4  4913.7 2094.53
  4920.8 2093.76  4926.5 2094.03  4936.4  2093.4    4959 2092.73  4970.5 2092.95
  4984.6 2091.01  4984.8 2090.51  4988.3 2090.51  4988.6 2091.01  4993.2 2092.25
  5002.1  2092.6  5015.6 2093.69  5023.2 2091.91  5029.8 2092.49  5037.4 2092.44
  5044.1 2093.69  5050.8 2096.43  5062.8 2097.41  5072.5 2097.64  5079.2 2098.38
  5083.1 2098.19  5093.4 2097.76  5121.9 2098.47  5129.5 2099.47  5135.4 2098.88
#Mann= 6 ,-1 , 0
  4867.7     .16       0  4890.8     .07       0  4984.6     .07       0
  4988.6     .07       0  5062.8     .16       0  5083.1     .07       0
Bank Sta=4984.6,4988.6
XS Rating Curve= 0 ,0
Exp/Cntr=0.3,0.1

Type RM Length L Ch R = 1 ,616     ,92,92,92
BEGIN DESCRIPTION:
Sweetwater Creek Trib 27 T4 1340
END DESCRIPTION:
XS GIS Cut Line= 3
      1376904.96      6877938.03      1377052.36      6877844.26
      1377138.06      6877722.49
#Sta/Elev= 30
  4825.3 2099.36  4859.8 2098.51  4872.8 2097.57  4905.8  2095.9  4911.7 2095.39
  4920.2 2095.15  4932.9 2094.21  4942.2 2092.33  4948.1 2092.04  4955.7 2090.28
  4963.4 2089.66  4978.6 2089.16  4984.5 2089.77  4989.3 2088.96  4989.5 2088.46
    4993 2088.46  4993.3 2088.96  4996.7    2089  5013.5 2089.71  5019.9 2091.25
  5028.3 2093.96  5034.4 2093.57  5043.1 2095.33  5056.6  2094.7  5070.2 2095.54
    5085  2095.7  5104.8 2096.63  5135.5 2097.61  5142.2  2097.6  5148.9 2098.06
#Mann= 7 ,-1 , 0
  4825.3     .07       0  4859.8     .16       0  4872.8     .07       0
  4989.3     .07       0  4993.3     .07       0  4996.7     .16       0
  5104.8     .07       0
Bank Sta=4989.3,4993.3
XS Rating Curve= 0 ,0
Exp/Cntr=0.3,0.1

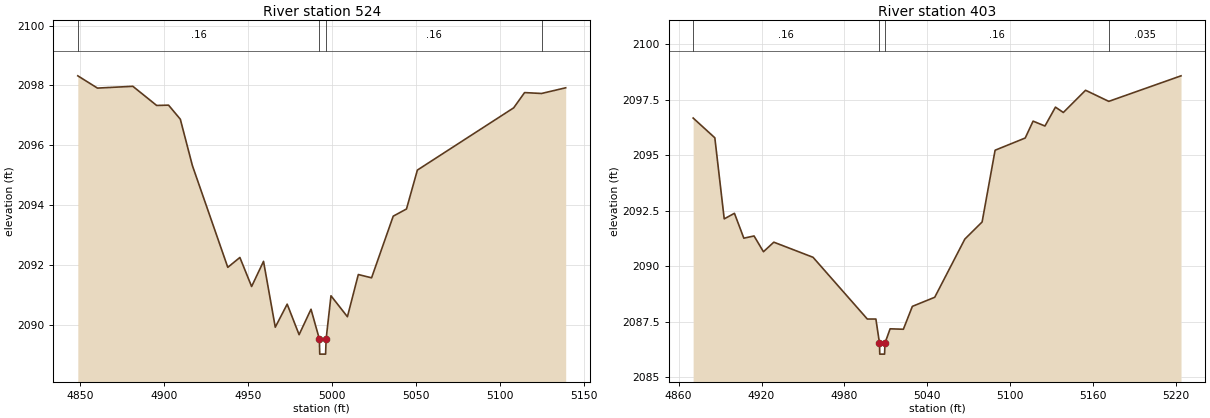
Type RM Length L Ch R = 1 ,524     ,121,121,121
BEGIN DESCRIPTION:
Sweetwater Creek Trib 27 T4 4009
END DESCRIPTION:
XS GIS Cut Line= 3
      1377002.78      6878002.29      1377111.03      6877896.17
      1377199.09      6877788.35
#Sta/Elev= 30
  4848.4 2098.32  4860.1 2097.91  4881.2 2097.97  4895.4 2097.33  4902.5 2097.34
  4909.5 2096.87  4916.7 2095.32  4937.8 2091.92    4945 2092.25    4952 2091.28
  4959.1 2092.12  4966.1 2089.92  4973.2 2090.69  4980.3 2089.67  4987.4 2090.52
  4992.4 2089.52  4992.6 2089.02  4996.1 2089.02  4996.4 2089.52  4999.3 2090.97
  5009.1 2090.27  5015.6 2091.68  5023.5 2091.57  5036.4 2093.63  5044.3 2093.87
  5050.8 2095.17  5108.2 2097.25  5114.7 2097.76  5124.8 2097.73  5139.2 2097.92
#Mann= 4 ,-1 , 0
  4848.4     .16       0  4992.4     .07       0  4996.4     .16       0
  5124.8     .07       0
Bank Sta=4992.4,4996.4
XS Rating Curve= 0 ,0
Exp/Cntr=0.3,0.1

Type RM Length L Ch R = 1 ,403     ,0,0,0
BEGIN DESCRIPTION:
Sweetwater Creek Trib 27 T4 4008
END DESCRIPTION:
XS GIS Cut Line= 3
      1377079.24      6878094.44      1377165.65      6877997.98
      1377272.57      6877801.49
#Sta/Elev= 30
  4870.5 2096.68  4886.2 2095.79    4893 2092.14  4900.4 2092.39  4907.2 2091.27
  4914.6 2091.37  4921.4 2090.66  4928.9 2091.09  4957.3 2090.41  4996.6 2087.63
  5002.8 2087.63  5005.4 2086.55  5005.6 2086.05  5009.1 2086.05  5009.4 2086.55
  5013.1 2087.19  5022.7 2087.17  5029.2  2088.2  5045.4 2088.61  5067.2 2091.23
  5079.7    2092  5089.1 2095.23  5110.9 2095.78  5116.6 2096.54  5125.2 2096.32
  5132.8 2097.17  5138.5 2096.93  5154.6 2097.93  5171.4 2097.43  5223.7 2098.58
#Mann= 4 ,-1 , 0
  4870.5     .16       0  5005.4     .07       0  5009.4     .16       0
  5171.4    .035       0
Bank Sta=5005.4,5009.4
XS Rating Curve= 0 ,0
Exp/Cntr=0.3,0.1

Chan Stop Cuts=-1
Use User Specified Reach Order=0
Composite Channel Slope=5