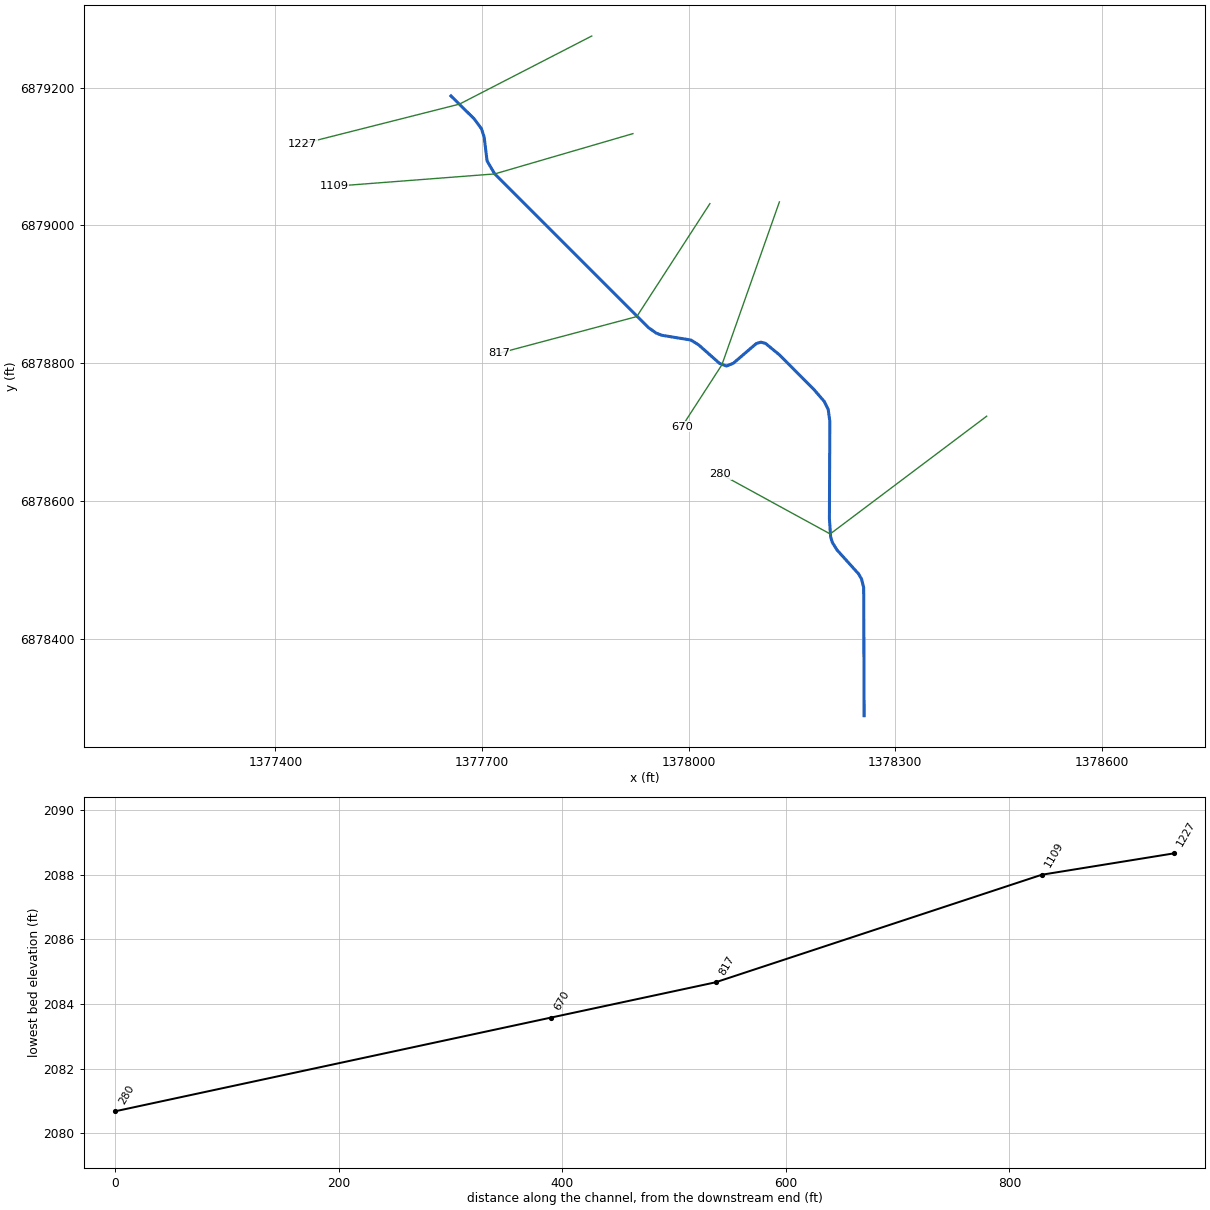
--- Sweetwater Creek Trib 27 T5.prj (project) ---

Proj Title=Sweetwater Creek Trib 27 T5 Base Level Engineering
Current Plan=p01
Default Exp/Contr=0.3,0.1
English Units
Geom File=g01
Flow File=f01
Plan File=p01
BEGIN DESCRIPTION:
Sweetwater Creek Trib 27 T5
END DESCRIPTION:

--- Sweetwater Creek Trib 27 T5.p01 (plan) ---

Plan Title=Multiple Run
Short Identifier=Multiple
Geom File=g01
Flow File=f01
Subcritical Flow
K Sum by GR= 0
Std Step Tol= 0.01
Critical Tol= 0.01
Num of Std Step Trials= 20
Max Error Tol= 0.3
Flow Tol Ratio= 0.001
Split Flow NTrial= 30
Split Flow Tol= 0.02
Split Flow Ratio= 0.02
Log Output Level= 0
Friction Slope Method= 1
Unsteady Friction Slope Method= 2
Unsteady Bridges Friction Slope Method= 1
Parabolic Critical Depth
Global Vel Dist=  1 , 1 , 1
Global Log Level= 0
CheckData=True
Encroach Param= -1, 0, 0, 0
BEGIN DESCRIPTION:
Multiple Run
END DESCRIPTION:

--- Sweetwater Creek Trib 27 T5.f01 (steady flow) ---

Flow Title=Multiple
Number of Profiles=7
Profile Names=10-year,25-year,50-year,1pct_min,100-year,1pct_plu,500-year
River Rch & RM= Sweetwater Creek,Reach-1,1227
     225     314     388     239     476     950     725
Boundary for River Rch & Prof#=Sweetwater Creek,Reach-1,1
Up Type=0
Dn Type=3
Dn Slope=0.005
Boundary for River Rch & Prof#=Sweetwater Creek,Reach-1,2
Up Type=0
Dn Type=3
Dn Slope=0.005
Boundary for River Rch & Prof#=Sweetwater Creek,Reach-1,3
Up Type=0
Dn Type=3
Dn Slope=0.005
Boundary for River Rch & Prof#=Sweetwater Creek,Reach-1,4
Up Type=0
Dn Type=3
Dn Slope=0.005
Boundary for River Rch & Prof#=Sweetwater Creek,Reach-1,5
Up Type=0
Dn Type=3
Dn Slope=0.005
Boundary for River Rch & Prof#=Sweetwater Creek,Reach-1,6
Up Type=0
Dn Type=3
Dn Slope=0.005
Boundary for River Rch & Prof#=Sweetwater Creek,Reach-1,7
Up Type=0
Dn Type=3
Dn Slope=0.005

--- Sweetwater Creek Trib 27 T5.g01 (geometry) ---

Geom Title=Existing Conditions

River Reach=Sweetwater Creek,Reach-1
Reach XY= 30
      1377655.00      6879188.00      1377688.58      6879154.92
      1377699.29      6879140.35      1377703.21      6879128.17
      1377707.45      6879093.56      1377718.57      6879074.77
      1377941.79      6878851.61      1377952.71      6878843.81
      1377961.05      6878840.46      1378003.35      6878833.56
      1378014.68      6878826.51      1378045.13      6878799.56
      1378055.09      6878795.78      1378065.05      6878799.84
      1378098.35      6878828.40      1378105.02      6878830.45
      1378111.69      6878828.71      1378131.73      6878812.26
      1378182.14      6878761.64      1378197.19      6878744.23
      1378202.83      6878732.57      1378205.20      6878715.36
      1378204.56      6878574.18      1378206.38      6878547.66
      1378208.78      6878539.57      1378215.85      6878528.35
      1378246.86      6878494.06      1378251.22      6878486.44
      1378254.33      6878474.08      1378255.00      6878288.00

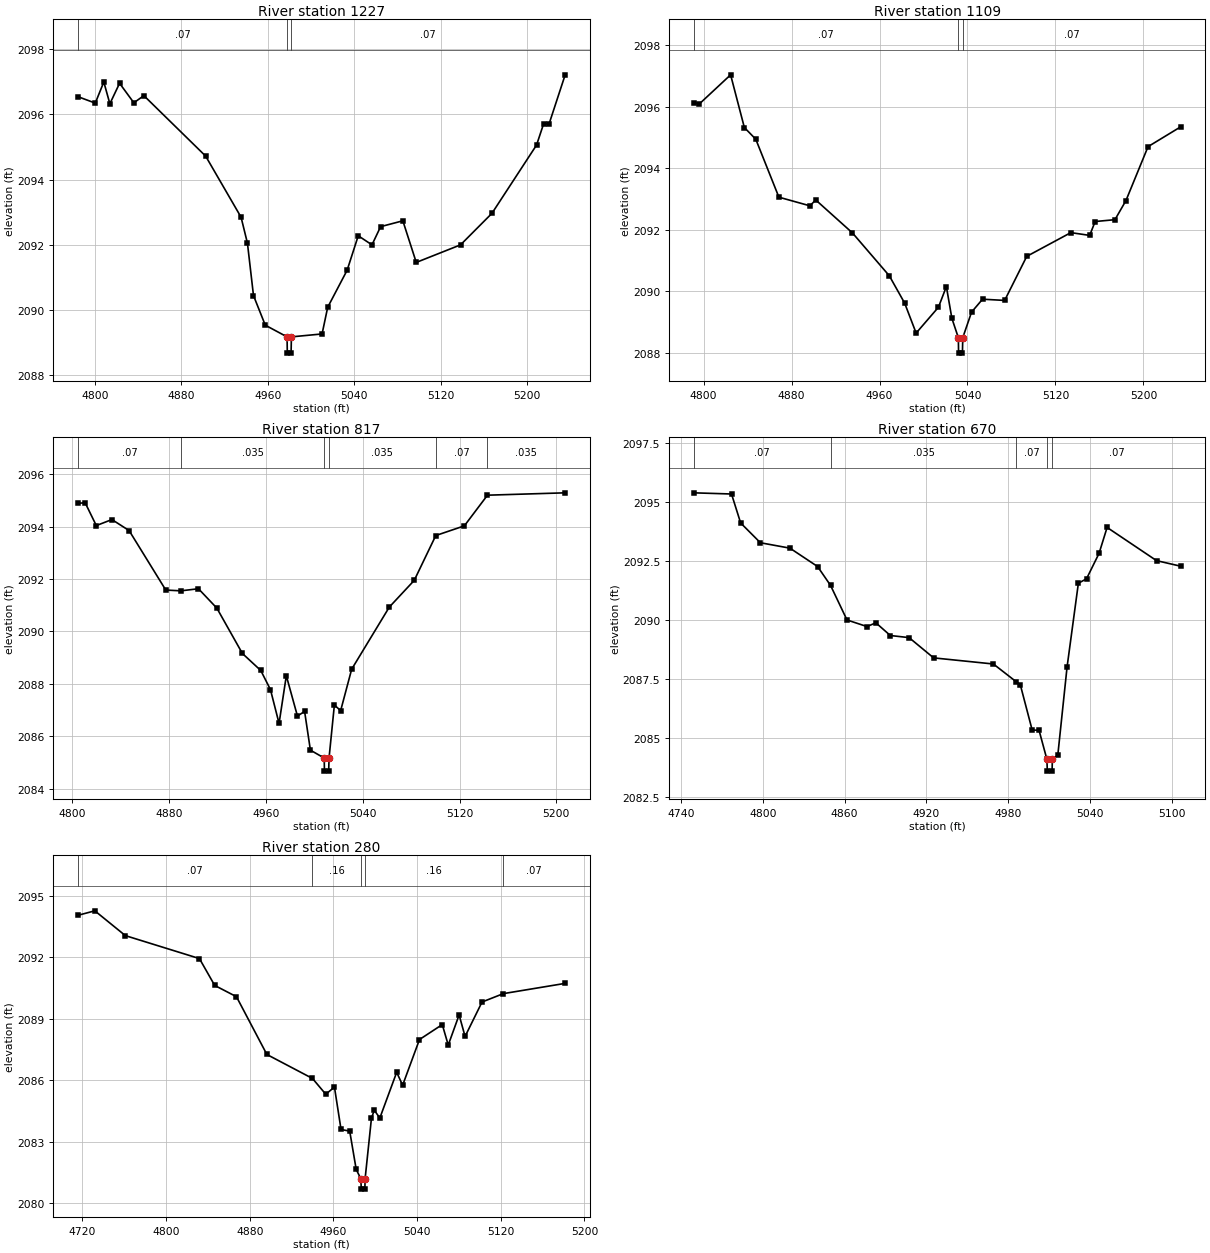
Type RM Length L Ch R = 1,1227,118,118,118
BEGIN DESCRIPTION:
Sweetwater Creek Trib 27 T5 4044
END DESCRIPTION:
XS GIS Cut Line= 3
      1377859.42      6879275.04      1377667.39      6879176.15
      1377439.27      6879118.43
#Sta/Elev= 30
  4784.0 2096.55  4800.2 2096.35  4808.1 2097.00  4813.7 2096.33  4822.7 2096.96
  4835.9 2096.36  4845.2 2096.58  4902.4 2094.72  4935.2 2092.84  4941.1 2092.04
  4946.7 2090.43  4957.6 2089.52  4977.8 2089.16  4978.0 2088.66  4981.5 2088.66
  4981.8 2089.16  5010.2 2089.25  5015.4 2090.07  5033.4 2091.21  5043.7 2092.27
  5056.4 2091.99  5064.4 2092.55  5085.0 2092.73  5097.4 2091.45  5138.4 2091.99
  5167.5 2092.96  5208.8 2095.06  5215.3 2095.71  5220.5 2095.72  5235.3 2097.22
#Mann=3,-1,0
  4784.0    0.07       0  4977.8    0.07       0  4981.8    0.07       0
Bank Sta=4977.8,4981.8
Exp/Cntr=0.3,0.1

Type RM Length L Ch R = 1,1109,292,292,292
BEGIN DESCRIPTION:
Sweetwater Creek Trib 27 T5 4043
END DESCRIPTION:
XS GIS Cut Line= 3
      1377919.22      6879133.27      1377718.57      6879074.77
      1377485.07      6879056.78
#Sta/Elev= 30
  4791.0 2096.12  4796.3 2096.09  4824.6 2097.03  4837.1 2095.32  4847.5 2094.94
  4868.5 2093.06  4896.7 2092.78  4902.0 2092.97  4935.4 2091.90  4968.9 2090.51
  4982.9 2089.62  4993.3 2088.65  5013.6 2089.49  5020.8 2090.16  5025.8 2089.13
  5031.7 2088.50  5031.9 2088.00  5035.4 2088.00  5035.7 2088.50  5043.7 2089.33
  5053.7 2089.75  5073.8 2089.71  5093.9 2091.14  5134.0 2091.91  5151.1 2091.82
  5156.1 2092.27  5174.1 2092.33  5184.1 2092.95  5204.2 2094.70  5234.2 2095.35
#Mann=3,-1,0
  4791.0    0.07       0  5031.7    0.07       0  5035.7    0.07       0
Bank Sta=5031.7,5035.7
Exp/Cntr=0.3,0.1

Type RM Length L Ch R = 1,817,147,147,147
BEGIN DESCRIPTION:
Sweetwater Creek Trib 27 T5 4042
END DESCRIPTION:
XS GIS Cut Line= 3
      1378031.02      6879031.64      1377924.84      6878867.61
      1377724.51      6878814.31
#Sta/Elev= 30
  4804.6 2094.89  4810.7 2094.91  4819.9 2094.04  4832.8 2094.27  4847.0 2093.85
  4877.3 2091.58  4889.8 2091.55  4904.3 2091.63  4919.5 2090.89  4940.6 2089.16
  4955.8 2088.51  4963.8 2087.78  4970.9 2086.49  4976.9 2088.31  4986.1 2086.77
  4992.0 2086.95  4996.8 2085.47  5008.2 2085.17  5008.4 2084.67  5011.9 2084.67
  5012.2 2085.17  5016.6 2087.19  5021.8 2086.98  5030.9 2088.56  5062.0 2090.93
  5082.6 2091.95  5100.4 2093.66  5124.0 2094.03  5143.1 2095.20  5207.3 2095.29
#Mann=6,-1,0
  4804.6    0.07       0  4889.8   0.035       0  5008.2   0.035       0
  5012.2   0.035       0  5100.4    0.07       0  5143.1   0.035       0
Bank Sta=5008.2,5012.2
Exp/Cntr=0.3,0.1

Type RM Length L Ch R = 1,670,390,390,390
BEGIN DESCRIPTION:
Sweetwater Creek Trib 27 T5 4041
END DESCRIPTION:
XS GIS Cut Line= 3
      1378131.95      6879034.18      1378048.45      6878797.59
      1377990.31      6878707.76
#Sta/Elev= 30
  4749.1 2095.40  4776.9 2095.35  4783.6 2094.12  4798.1 2093.28  4819.8 2093.05
  4840.1 2092.27  4849.6 2091.47  4861.7 2090.00  4876.4 2089.72  4882.9 2089.88
  4893.5 2089.34  4907.3 2089.25  4925.3 2088.39  4969.2 2088.13  4986.1 2087.37
  4989.0 2087.24  4997.7 2085.32  5002.7 2085.32  5008.5 2084.08  5008.8 2083.58
  5012.3 2083.58  5012.5 2084.08  5016.5 2084.26  5023.3 2088.00  5031.6 2091.56
  5037.6 2091.75  5046.8 2092.83  5052.7 2093.93  5089.0 2092.52  5107.0 2092.28
#Mann=5,-1,0
  4749.1    0.07       0  4849.6   0.035       0  4986.1    0.07       0
  5008.5    0.07       0  5012.5    0.07       0
Bank Sta=5008.5,5012.5
Exp/Cntr=0.3,0.1

Type RM Length L Ch R = 1,280,0,0,0
BEGIN DESCRIPTION:
Sweetwater Creek Trib 27 T5 4045
END DESCRIPTION:
XS GIS Cut Line= 3
      1378432.94      6878722.91      1378205.69      6878551.92
      1378046.36      6878639.06
#Sta/Elev= 30
  4715.6 2094.04  4731.9 2094.26  4761.1 2093.05  4831.9 2091.93  4846.5 2090.62
  4867.3 2090.07  4896.4 2087.25  4940.0 2086.08  4952.7 2085.31  4961.0 2085.66
  4967.3 2083.59  4975.6 2083.51  4981.8 2081.64  4986.3 2081.18  4986.6 2080.68
  4990.1 2080.68  4990.3 2081.18  4996.4 2084.15  4999.1 2084.53  5004.4 2084.15
  5020.5 2086.38  5026.2 2085.75  5042.3 2087.98  5064.1 2088.71  5069.8 2087.71
  5080.2 2089.18  5085.9 2088.13  5102.1 2089.81  5122.5 2090.22  5181.6 2090.72
#Mann=5,-1,0
  4715.6    0.07       0  4940.0    0.16       0  4986.3    0.07       0
  4990.3    0.16       0  5122.5    0.07       0
Bank Sta=4986.3,4990.3
Exp/Cntr=0.3,0.1

Chan Stop Cuts=-1