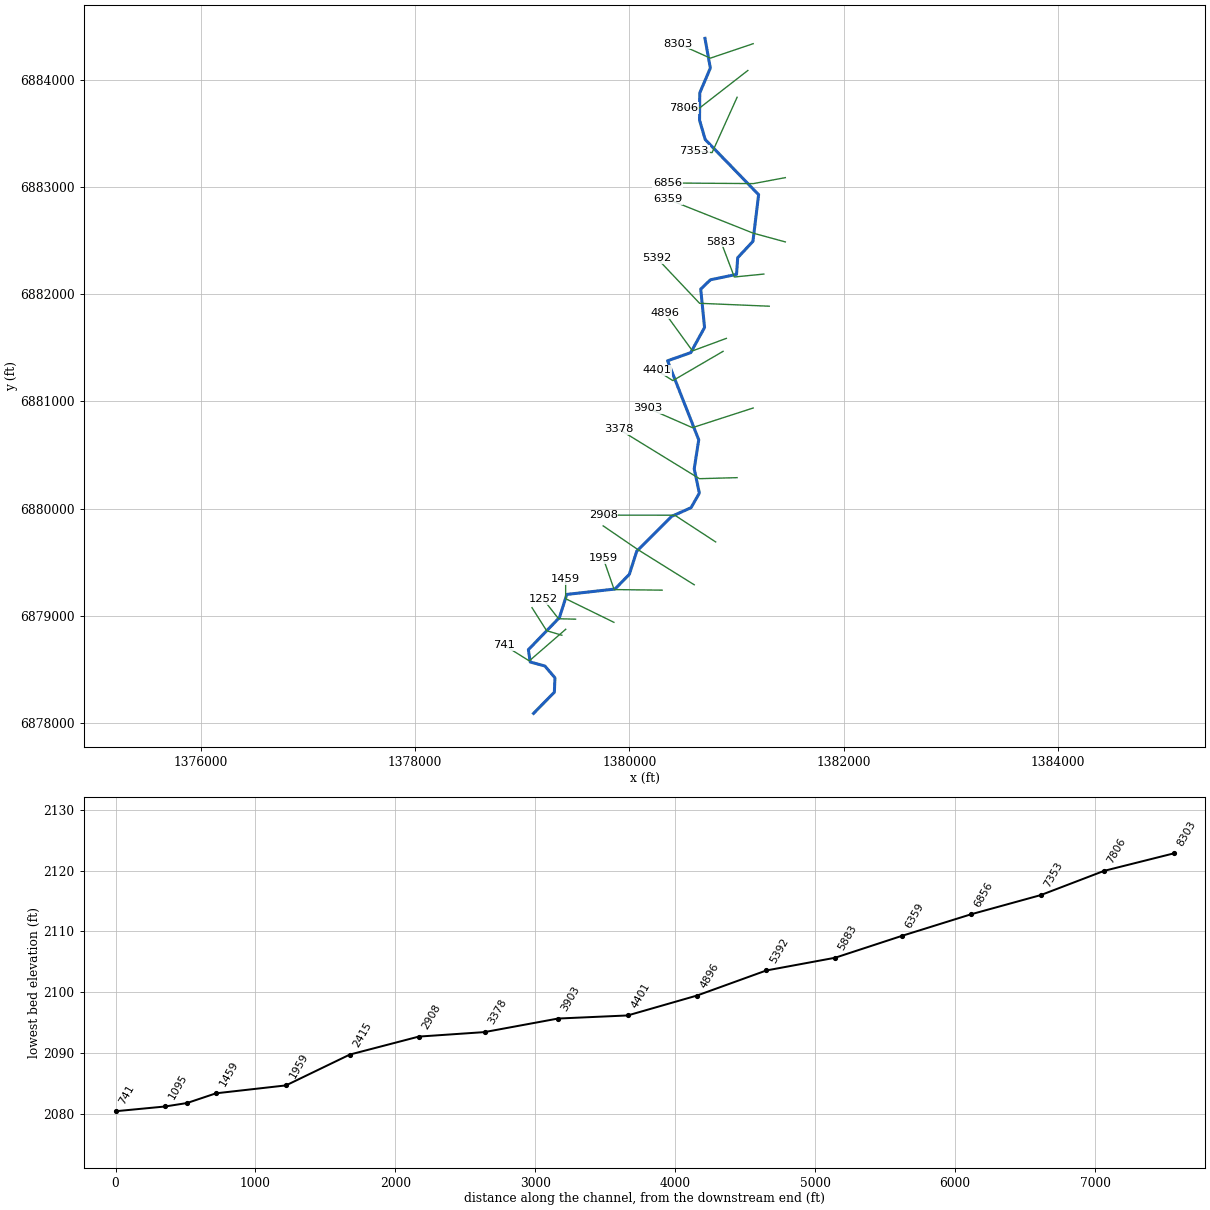
--- Sweetwater Creek Trib 27 T6.prj (project) ---

Proj Title=Sweetwater Creek Trib 27 T6 Base Level Engineering
Current Plan=p01
Default Exp/Contr=0.3,0.1
English Units
Geom File=g01
Flow File=f01
Plan File=p01
BEGIN DESCRIPTION:
Sweetwater Creek Trib 27 T6
END DESCRIPTION:

--- Sweetwater Creek Trib 27 T6.p01 (plan) ---

Plan Title=Multiple Run
Short Identifier=Multiple
Geom File=g01
Flow File=f01
Subcritical Flow
K Sum by GR= 0
Std Step Tol= 0.01
Critical Tol= 0.01
Num of Std Step Trials= 20
Max Error Tol= 0.3
Flow Tol Ratio= 0.001
Split Flow NTrial= 30
Split Flow Tol= 0.02
Split Flow Ratio= 0.02
Log Output Level= 0
Friction Slope Method= 1
Unsteady Friction Slope Method= 2
Unsteady Bridges Friction Slope Method= 1
Parabolic Critical Depth
Global Vel Dist=  1 , 1 , 1
Global Log Level= 0
CheckData=True
Encroach Param= -1, 0, 0, 0
BEGIN DESCRIPTION:
Multiple Run
END DESCRIPTION:

--- Sweetwater Creek Trib 27 T6.f01 (steady flow) ---

Flow Title=Multiple
Number of Profiles=7
Profile Names=10-year,25-year,50-year,1pct_min,100-year,1pct_plu,500-year
River Rch & RM= Sweetwater Creek,Reach-1,8303
     382     550     692     433     863    1722    1361
Boundary for River Rch & Prof#=Sweetwater Creek,Reach-1,1
Up Type=0
Dn Type=3
Dn Slope=0.005
Boundary for River Rch & Prof#=Sweetwater Creek,Reach-1,2
Up Type=0
Dn Type=3
Dn Slope=0.005
Boundary for River Rch & Prof#=Sweetwater Creek,Reach-1,3
Up Type=0
Dn Type=3
Dn Slope=0.005
Boundary for River Rch & Prof#=Sweetwater Creek,Reach-1,4
Up Type=0
Dn Type=3
Dn Slope=0.005
Boundary for River Rch & Prof#=Sweetwater Creek,Reach-1,5
Up Type=0
Dn Type=3
Dn Slope=0.005
Boundary for River Rch & Prof#=Sweetwater Creek,Reach-1,6
Up Type=0
Dn Type=3
Dn Slope=0.005
Boundary for River Rch & Prof#=Sweetwater Creek,Reach-1,7
Up Type=0
Dn Type=3
Dn Slope=0.005

--- Sweetwater Creek Trib 27 T6.g01 (geometry) ---

Geom Title=Existing Conditions

River Reach=Sweetwater Creek,Reach-1
Reach XY= 30
      1380705.00      6884388.00      1380755.12      6884110.70
      1380656.38      6883878.34      1380654.56      6883624.18
      1380707.44      6883443.56      1381205.81      6882928.89
      1381152.83      6882493.44      1381010.47      6882340.45
      1380999.65      6882185.26      1380756.45      6882134.47
      1380665.46      6882047.82      1380701.26      6881689.56
      1380572.05      6881454.47      1380356.09      6881378.70
      1380646.96      6880641.32      1380604.61      6880369.66
      1380652.77      6880143.93      1380575.48      6880007.62
      1380395.30      6879927.24      1380068.39      6879601.33
      1379999.17      6879385.70      1379864.80      6879248.48
      1379415.36      6879198.16      1379346.86      6878981.94
      1379057.07      6878682.51      1379074.38      6878567.36
      1379211.19      6878530.14      1379304.93      6878419.78
      1379299.55      6878285.55      1379105.00      6878088.00

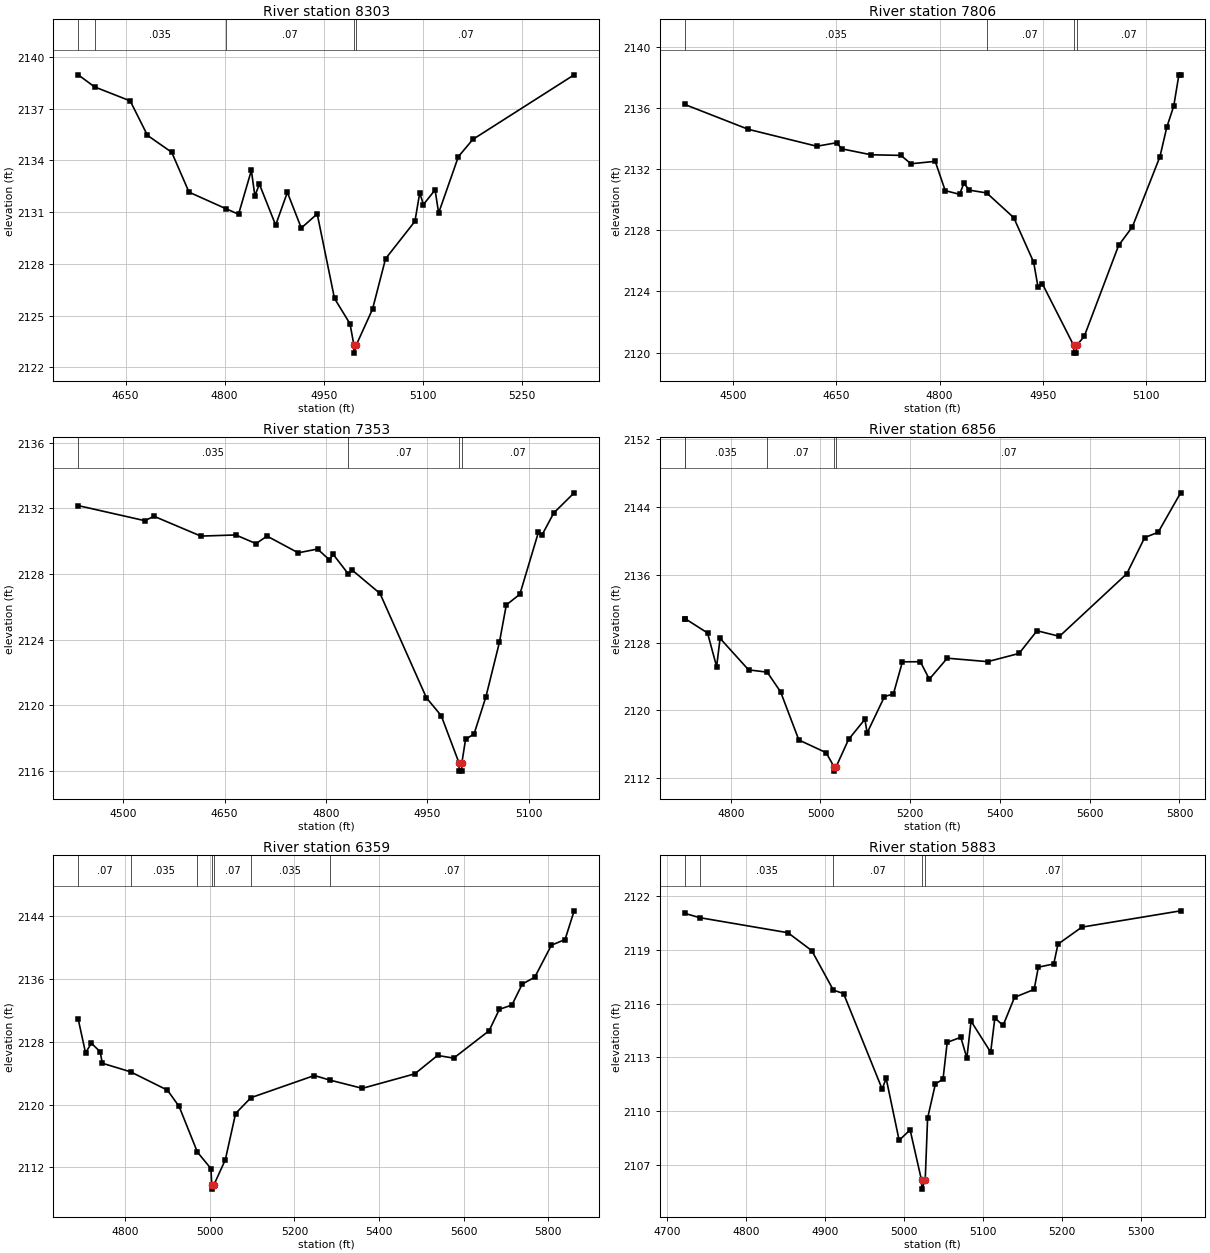
Type RM Length L Ch R = 1,8303,497,497,497
BEGIN DESCRIPTION:
Sweetwater Creek Trib 27 T6 15.0
END DESCRIPTION:
XS GIS Cut Line= 3
      1381155.03      6884338.01      1380755.47      6884203.16
      1380455.04      6884337.98
#Sta/Elev= 30
  4578.3 2138.96  4603.1 2138.26  4657.0 2137.45  4683.2 2135.45  4719.9 2134.47
  4746.1 2132.16  4801.4 2131.21  4821.1 2130.88  4840.5 2133.42  4845.8 2131.95
  4852.7 2132.62  4877.3 2130.25  4895.0 2132.15  4916.1 2130.08  4940.2 2130.90
  4966.4 2126.00  4989.9 2124.53  4995.6 2123.33  4995.8 2122.83  4999.7 2123.33
  5024.0 2125.38  5043.7 2128.30  5088.2 2130.47  5095.5 2132.13  5101.0 2131.44
  5118.7 2132.29  5124.1 2130.95  5154.0 2134.22  5176.0 2135.22  5329.3 2138.96
#Mann=5,-1,0
  4578.3    0.07       0  4603.1   0.035       0  4801.4    0.07       0
  4995.6    0.07       0  4999.7    0.07       0
Bank Sta=4995.6,4999.7
Exp/Cntr=0.3,0.1

Type RM Length L Ch R = 1,7806,453,453,453
BEGIN DESCRIPTION:
Sweetwater Creek Trib 27 T6 14.0
END DESCRIPTION:
XS GIS Cut Line= 3
      1381105.00      6884088.00      1380654.98      6883738.00
      1380504.98      6883738.00
#Sta/Elev= 30
  4429.9 2136.26  4522.2 2134.63  4621.7 2133.52  4650.7 2133.75  4657.9 2133.35
  4700.5 2132.96  4743.9 2132.92  4758.4 2132.37  4793.7 2132.53  4808.2 2130.61
  4829.0 2130.37  4835.3 2131.09  4843.4 2130.64  4868.4 2130.46  4907.7 2128.84
  4936.6 2125.92  4943.0 2124.28  4949.3 2124.50  4994.8 2120.46  4995.0 2119.96
  4998.6 2119.96  4998.9 2120.46  5010.0 2121.05  5060.0 2127.02  5080.0 2128.24
  5120.0 2132.84  5130.0 2134.78  5140.0 2136.15  5147.5 2138.20  5150.0 2138.20
#Mann=4,-1,0
  4429.9   0.035       0  4868.4    0.07       0  4994.8    0.07       0
  4998.9    0.07       0
Bank Sta=4994.8,4998.9
Exp/Cntr=0.3,0.1

Type RM Length L Ch R = 1,7353,497,497,497
BEGIN DESCRIPTION:
Sweetwater Creek Trib 27 T6 13.0
END DESCRIPTION:
XS GIS Cut Line= 3
      1381004.99      6883837.97      1380771.64      6883321.32
      1380604.97      6883338.00
#Sta/Elev= 30
  4433.1 2132.17  4531.8 2131.25  4545.3 2131.52  4614.7 2130.31  4666.4 2130.38
  4696.4 2129.85  4712.7 2130.31  4758.9 2129.29  4787.5 2129.52  4805.1 2128.86
  4810.6 2129.20  4832.7 2128.02  4839.2 2128.22  4880.0 2126.81  4948.8 2120.44
  4970.7 2119.35  4997.0 2116.47  4997.3 2115.97  5000.9 2115.97  5001.2 2116.47
  5006.7 2117.91  5019.3 2118.24  5036.8 2120.50  5056.9 2123.84  5067.0 2126.11
  5087.1 2126.76  5114.7 2130.56  5119.8 2130.37  5137.3 2131.72  5167.5 2132.95
#Mann=4,-1,0
  4433.1   0.035       0  4832.7    0.07       0  4997.0    0.07       0
  5001.2    0.07       0
Bank Sta=4997,5001.2
Exp/Cntr=0.3,0.1

Type RM Length L Ch R = 1,6856,497,497,497
BEGIN DESCRIPTION:
Sweetwater Creek Trib 27 T6 12.0
END DESCRIPTION:
XS GIS Cut Line= 3
      1381455.01      6883088.00      1381157.59      6883032.28
      1380355.01      6883038.00
#Sta/Elev= 30
  4697.4 2130.80  4699.2 2130.80  4748.3 2129.14  4768.6 2125.16  4776.3 2128.50
  4839.8 2124.78  4881.3 2124.51  4911.1 2122.19  4951.8 2116.50  5012.6 2115.00
  5030.4 2113.32  5030.7 2112.82  5034.8 2113.32  5062.6 2116.56  5099.0 2118.94
  5104.0 2117.33  5142.6 2121.62  5162.6 2121.94  5182.6 2125.73  5222.6 2125.74
  5242.6 2123.68  5282.6 2126.16  5372.6 2125.75  5442.6 2126.72  5482.6 2129.40
  5532.6 2128.74  5682.6 2136.13  5722.6 2140.41  5752.6 2141.03  5802.6 2145.69
#Mann=5,-1,0
  4697.4    0.07       0  4699.2   0.035       0  4881.3    0.07       0
  5030.4    0.07       0  5034.8    0.07       0
Bank Sta=5030.4,5034.8
Exp/Cntr=0.3,0.1

Type RM Length L Ch R = 1,6359,476,476,476
BEGIN DESCRIPTION:
Sweetwater Creek Trib 27 T6 11.0
END DESCRIPTION:
XS GIS Cut Line= 3
      1381455.02      6882487.99      1381155.16      6882569.75
      1380355.03      6882887.99
#Sta/Elev= 30
  4689.2 2130.86  4706.5 2126.57  4720.3 2127.79  4741.0 2126.71  4746.2 2125.25
  4812.8 2124.16  4900.0 2121.83  4927.6 2119.76  4970.8 2113.96  5002.8 2111.86
  5004.8 2109.75  5005.2 2109.25  5009.5 2109.75  5036.8 2112.98  5061.1 2118.86
  5097.3 2120.87  5247.3 2123.69  5283.0 2123.12  5360.6 2122.06  5484.5 2123.90
  5538.3 2126.24  5576.5 2125.90  5660.1 2129.38  5684.4 2132.10  5714.1 2132.65
  5738.4 2135.31  5768.0 2136.18  5807.3 2140.25  5839.6 2140.97  5861.1 2144.62
#Mann=7,-1,0
  4689.2    0.07       0  4812.8   0.035       0  4970.8    0.07       0
  5004.8    0.07       0  5009.5    0.07       0  5097.3   0.035       0
  5283.0    0.07       0
Bank Sta=5004.8,5009.5
Exp/Cntr=0.3,0.1

Type RM Length L Ch R = 1,5883,491,491,491
BEGIN DESCRIPTION:
Sweetwater Creek Trib 27 T6 10.0
END DESCRIPTION:
XS GIS Cut Line= 3
      1381254.98      6882188.00      1380979.03      6882160.65
      1380854.99      6882488.04
#Sta/Elev= 30
  4722.7 2121.03  4741.6 2120.79  4853.3 2119.95  4883.5 2118.95  4910.8 2116.75
  4923.7 2116.56  4972.5 2111.24  4977.6 2111.83  4994.0 2108.38  5007.9 2108.96
  5022.3 2106.16  5022.7 2105.66  5027.0 2106.16  5030.0 2109.61  5039.9 2111.53
  5049.5 2111.78  5054.8 2113.84  5072.0 2114.12  5079.7 2112.97  5085.0 2115.02
  5109.8 2113.29  5115.1 2115.20  5125.5 2114.78  5140.0 2116.35  5164.8 2116.79
  5170.1 2118.03  5189.6 2118.21  5194.9 2119.31  5225.1 2120.26  5350.1 2121.17
#Mann=5,-1,0
  4722.7    0.07       0  4741.6   0.035       0  4910.8    0.07       0
  5022.3    0.07       0  5027.0    0.07       0
Bank Sta=5022.3,5027
Exp/Cntr=0.3,0.1

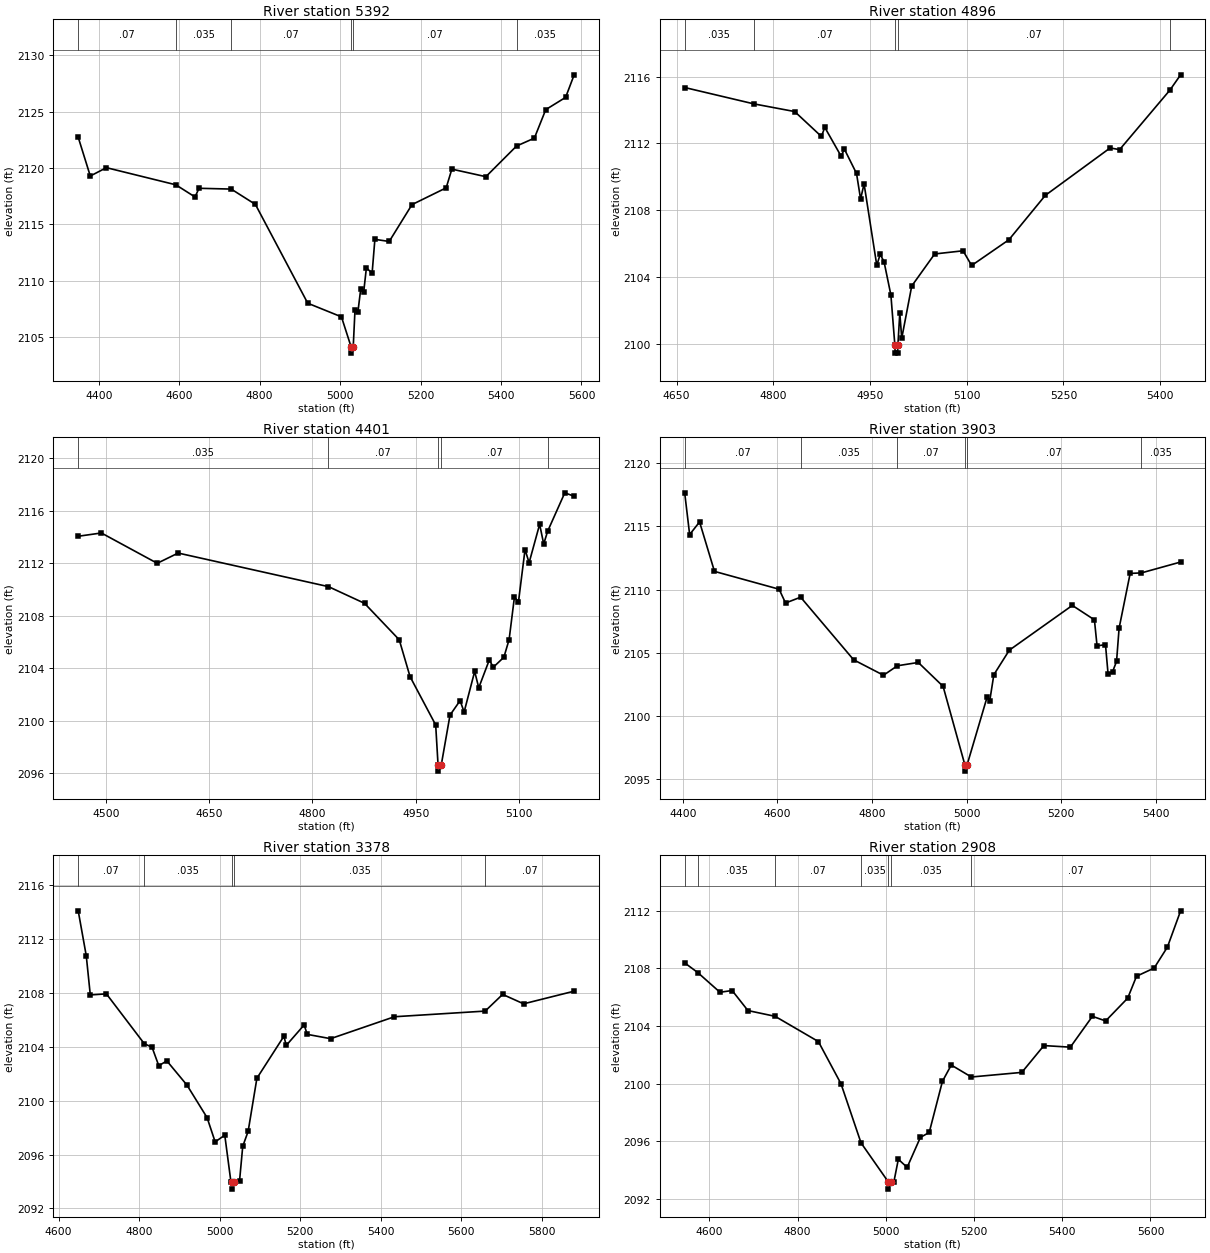
Type RM Length L Ch R = 1,5392,496,496,496
BEGIN DESCRIPTION:
Sweetwater Creek Trib 27 T6 9.0
END DESCRIPTION:
XS GIS Cut Line= 3
      1381305.02      6881888.00      1380654.69      6881915.17
      1380255.03      6882337.97
#Sta/Elev= 30
  4349.1 2122.73  4379.1 2119.29  4419.2 2120.03  4591.7 2118.51  4639.4 2117.43
  4649.4 2118.20  4729.4 2118.13  4789.5 2116.77  4919.6 2108.00  5003.4 2106.79
  5027.9 2104.07  5028.2 2103.57  5032.6 2104.07  5037.1 2107.42  5044.4 2107.25
  5051.3 2109.26  5058.6 2108.97  5065.4 2111.14  5079.6 2110.66  5086.5 2113.67
  5122.1 2113.48  5178.7 2116.75  5263.7 2118.24  5277.8 2119.90  5362.4 2119.23
  5438.6 2121.95  5482.9 2122.65  5511.2 2125.18  5560.6 2126.27  5581.8 2128.27
#Mann=6,-1,0
  4349.1    0.07       0  4591.7   0.035       0  4729.4    0.07       0
  5027.9    0.07       0  5032.6    0.07       0  5438.6   0.035       0
Bank Sta=5027.9,5032.6
Exp/Cntr=0.3,0.1

Type RM Length L Ch R = 1,4896,495,495,495
BEGIN DESCRIPTION:
Sweetwater Creek Trib 27 T6 8.0
END DESCRIPTION:
XS GIS Cut Line= 3
      1380904.96      6881587.99      1380588.51      6881470.94
      1380334.93      6881820.32
#Sta/Elev= 30
  4662.6 2115.35  4769.9 2114.37  4833.2 2113.91  4874.6 2112.42  4879.9 2112.96
  4905.0 2111.25  4910.4 2111.65  4929.1 2110.20  4935.4 2108.67  4940.8 2109.58
  4960.5 2104.70  4965.8 2105.36  4971.8 2104.91  4982.4 2102.92  4988.5 2099.94
  4988.9 2099.44  4993.0 2099.44  4993.3 2099.94  4996.2 2101.85  4999.2 2100.33
  5014.7 2103.46  5050.3 2105.38  5094.3 2105.57  5107.6 2104.69  5165.4 2106.23
  5221.9 2108.89  5322.4 2111.73  5337.1 2111.63  5415.2 2115.20  5431.7 2116.11
#Mann=5,-1,0
  4662.6   0.035       0  4769.9    0.07       0  4988.5    0.07       0
  4993.3    0.07       0  5415.2   0.035       0
Bank Sta=4988.5,4993.3
Exp/Cntr=0.3,0.1

Type RM Length L Ch R = 1,4401,498,498,498
BEGIN DESCRIPTION:
Sweetwater Creek Trib 27 T6 7.0
END DESCRIPTION:
XS GIS Cut Line= 3
      1380874.06      6881466.82      1380405.61      6881193.75
      1380255.00      6881288.00
#Sta/Elev= 30
  4460.0 2114.07  4493.6 2114.32  4574.7 2112.01  4605.1 2112.79  4823.3 2110.23
  4875.6 2108.96  4926.0 2106.18  4941.7 2103.37  4978.9 2099.69  4982.3 2096.67
  4982.7 2096.17  4987.1 2096.67  4999.7 2100.44  5014.3 2101.54  5020.2 2100.68
  5035.5 2103.77  5041.4 2102.52  5056.7 2104.64  5062.6 2104.09  5077.9 2104.85
  5085.5 2106.20  5093.2 2109.43  5099.1 2109.08  5108.6 2113.06  5114.5 2112.05
  5129.8 2114.98  5135.7 2113.48  5141.4 2114.45  5166.3 2117.38  5179.9 2117.12
#Mann=5,-1,0
  4460.0   0.035       0  4823.3    0.07       0  4982.3    0.07       0
  4987.1    0.07       0  5141.4   0.035       0
Bank Sta=4982.3,4987.1
Exp/Cntr=0.3,0.1

Type RM Length L Ch R = 1,3903,525,525,525
BEGIN DESCRIPTION:
Sweetwater Creek Trib 27 T6 6.0
END DESCRIPTION:
XS GIS Cut Line= 3
      1381154.96      6880937.99      1380587.91      6880754.48
      1380173.18      6880936.21
#Sta/Elev= 30
  4404.0 2117.66  4414.5 2114.36  4435.5 2115.36  4467.0 2111.45  4603.7 2110.04
  4617.3 2108.95  4649.2 2109.41  4761.3 2104.46  4824.4 2103.24  4853.9 2103.99
  4898.0 2104.25  4950.5 2102.36  4996.5 2096.16  4996.9 2095.66  5001.3 2096.16
  5043.8 2101.54  5049.2 2101.23  5057.8 2103.28  5090.5 2105.22  5223.8 2108.76
  5270.5 2107.62  5276.1 2105.56  5293.9 2105.66  5299.4 2103.33  5308.9 2103.52
  5317.3 2104.33  5322.7 2106.96  5346.1 2111.29  5369.8 2111.33  5452.8 2112.19
#Mann=6,-1,0
  4404.0    0.07       0  4649.2   0.035       0  4853.9    0.07       0
  4996.5    0.07       0  5001.3    0.07       0  5369.8   0.035       0
Bank Sta=4996.5,5001.3
Exp/Cntr=0.3,0.1

Type RM Length L Ch R = 1,3378,470,470,470
BEGIN DESCRIPTION:
Sweetwater Creek Trib 27 T6 5.0
END DESCRIPTION:
XS GIS Cut Line= 3
      1381005.00      6880288.00      1380653.63      6880278.33
      1379903.61      6880739.00
#Sta/Elev= 30
  4648.5 2114.11  4668.5 2110.77  4678.5 2107.86  4718.5 2107.94  4812.5 2104.24
  4831.9 2103.97  4848.6 2102.60  4868.6 2102.96  4918.6 2101.16  4968.6 2098.74
  4988.6 2096.94  5012.5 2097.44  5027.9 2093.94  5031.1 2093.93  5031.5 2093.43
  5036.3 2093.93  5049.2 2094.05  5057.1 2096.61  5070.5 2097.72  5092.3 2101.67
  5159.3 2104.79  5165.2 2104.11  5209.6 2105.63  5217.3 2104.93  5275.3 2104.61
  5433.9 2106.24  5659.2 2106.66  5702.6 2107.90  5754.7 2107.20  5880.2 2108.14
#Mann=5,-1,0
  4648.5    0.07       0  4812.5   0.035       0  5031.1   0.035       0
  5036.3   0.035       0  5659.2    0.07       0
Bank Sta=5031.1,5036.3
Exp/Cntr=0.3,0.1

Type RM Length L Ch R = 1,2908,493,493,493
BEGIN DESCRIPTION:
Sweetwater Creek Trib 27 T6 4.0
END DESCRIPTION:
XS GIS Cut Line= 3
      1380805.04      6879687.97      1380423.38      6879937.52
      1379754.98      6879938.00
#Sta/Elev= 30
  4544.0 2108.39  4573.9 2107.71  4624.0 2106.35  4651.6 2106.47  4687.4 2105.08
  4749.0 2104.68  4847.1 2102.93  4898.4 2100.00  4943.8 2095.90  5005.7 2093.19
  5006.1 2092.69  5011.0 2093.19  5018.4 2093.21  5028.4 2094.76  5048.4 2094.20
  5078.4 2096.28  5098.4 2096.62  5128.4 2100.17  5148.4 2101.30  5194.0 2100.47
  5308.4 2100.79  5358.4 2102.65  5418.4 2102.54  5468.4 2104.68  5498.4 2104.36
  5548.4 2105.94  5568.4 2107.46  5608.4 2108.03  5638.4 2109.48  5668.4 2112.00
#Mann=7,-1,0
  4544.0    0.07       0  4573.9   0.035       0  4749.0    0.07       0
  4943.8   0.035       0  5005.7   0.035       0  5011.0   0.035       0
  5194.0    0.07       0
Bank Sta=5005.7,5011
Exp/Cntr=0.3,0.1

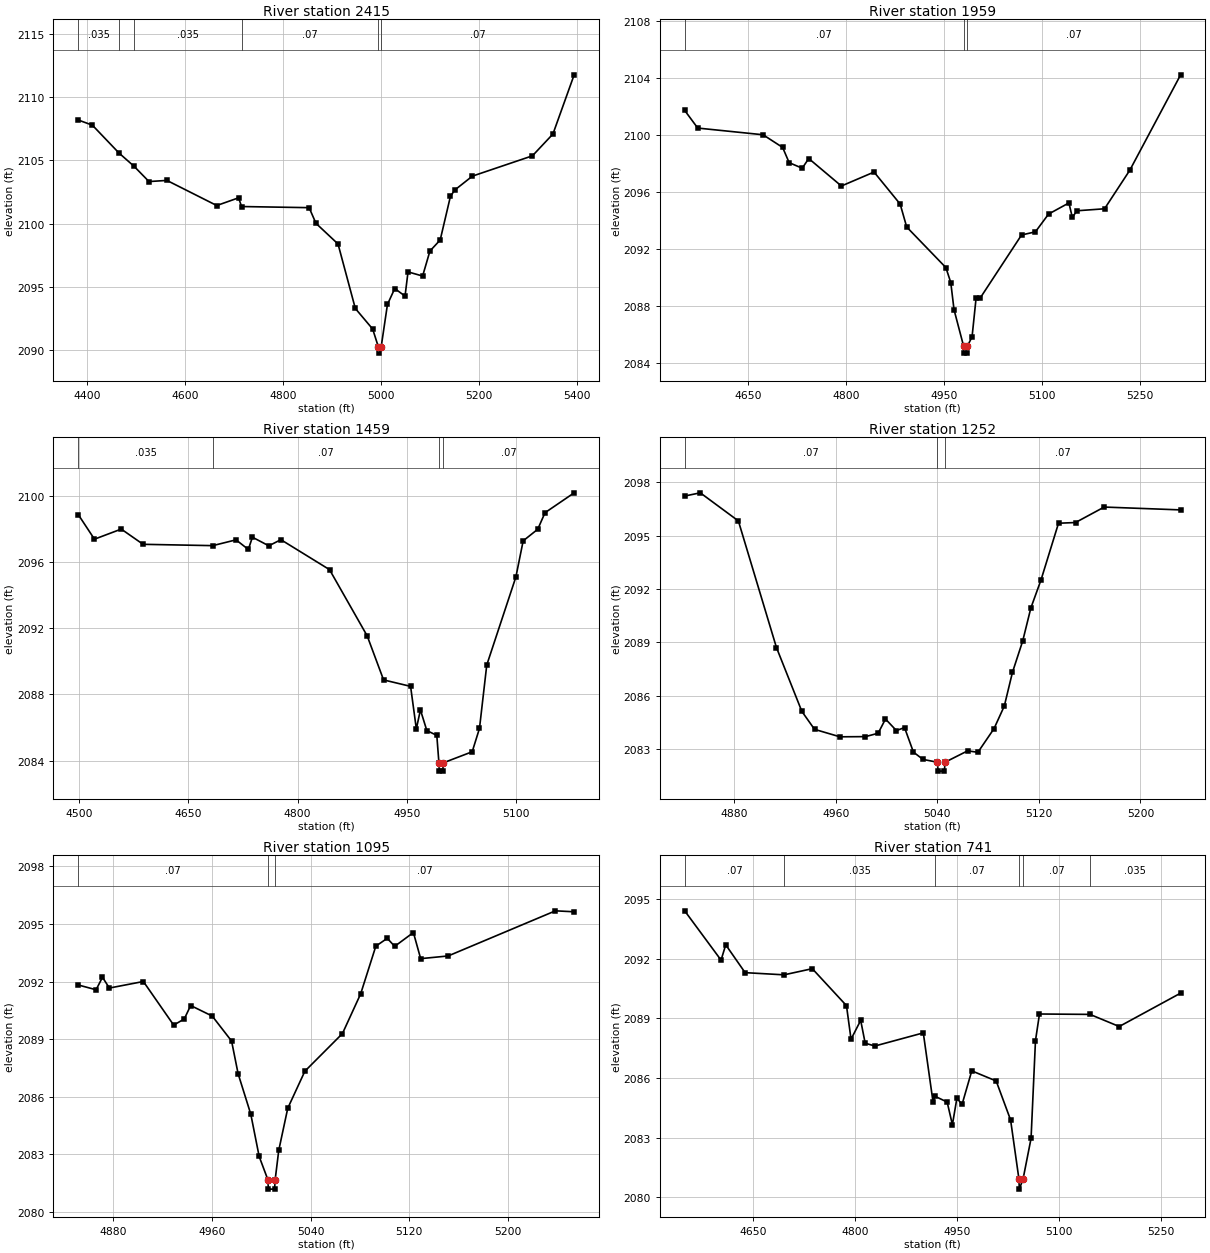
Type RM Length L Ch R = 1,2415,456,456,456
BEGIN DESCRIPTION:
Sweetwater Creek Trib 27 T6 3.0
END DESCRIPTION:
XS GIS Cut Line= 3
      1380605.01      6879288.00      1380081.15      6879614.93
      1379755.03      6879837.98
#Sta/Elev= 30
  4382.5 2108.21  4411.4 2107.80  4465.8 2105.59  4496.8 2104.53  4527.0 2103.33
  4563.6 2103.42  4665.4 2101.43  4709.9 2102.04  4716.1 2101.35  4854.0 2101.26
  4867.9 2100.02  4913.0 2098.38  4948.3 2093.27  4983.7 2091.64  4995.3 2090.23
  4995.7 2089.73  5001.1 2090.23  5013.9 2093.59  5028.8 2094.85  5049.8 2094.25
  5055.9 2096.17  5085.7 2095.84  5100.6 2097.82  5121.6 2098.70  5142.5 2102.16
  5151.4 2102.66  5187.3 2103.76  5309.9 2105.37  5351.8 2107.10  5395.1 2111.79
#Mann=6,-1,0
  4382.5   0.035       0  4465.8    0.07       0  4496.8   0.035       0
  4716.1    0.07       0  4995.3    0.07       0  5001.1    0.07       0
Bank Sta=4995.3,5001.1
Exp/Cntr=0.3,0.1

Type RM Length L Ch R = 1,1959,500,500,500
BEGIN DESCRIPTION:
Sweetwater Creek Trib 27 T6 2.0
END DESCRIPTION:
XS GIS Cut Line= 3
      1380305.02      6879238.00      1379857.45      6879243.46
      1379754.98      6879538.05
#Sta/Elev= 30
  4552.4 2101.71  4572.4 2100.47  4672.4 2100.00  4702.4 2099.11  4712.4 2098.04
  4732.4 2097.65  4742.4 2098.33  4792.4 2096.40  4842.4 2097.38  4882.4 2095.13
  4892.4 2093.52  4952.4 2090.67  4959.9 2089.62  4964.9 2087.71  4979.5 2085.16
  4980.0 2084.66  4984.9 2084.66  4985.4 2085.16  4992.5 2085.80  4998.7 2088.54
  5005.1 2088.54  5068.3 2092.96  5089.5 2093.18  5109.7 2094.43  5140.8 2095.21
  5146.1 2094.19  5153.0 2094.66  5195.4 2094.80  5234.1 2097.51  5311.9 2104.21
#Mann=3,-1,0
  4552.4    0.07       0  4979.5    0.07       0  4985.4    0.07       0
Bank Sta=4979.5,4985.4
Exp/Cntr=0.3,0.1

Type RM Length L Ch R = 1,1459,207,207,207
BEGIN DESCRIPTION:
Sweetwater Creek Trib 27 T6 1.0
END DESCRIPTION:
XS GIS Cut Line= 3
      1379855.03      6878937.99      1379404.78      6879158.16
      1379405.00      6879337.96
#Sta/Elev= 30
  4498.8 2098.86  4521.1 2097.37  4557.9 2097.98  4587.9 2097.06  4683.5 2096.98
  4715.5 2097.33  4732.4 2096.75  4738.0 2097.49  4760.5 2096.97  4777.1 2097.34
  4843.9 2095.53  4895.6 2091.53  4918.1 2088.87  4955.2 2088.48  4963.1 2085.91
  4968.7 2087.06  4977.5 2085.81  4991.2 2085.52  4994.1 2083.86  4994.6 2083.36
  4999.6 2083.36  5000.0 2083.86  5039.8 2084.53  5049.8 2085.94  5059.8 2089.77
  5099.8 2095.09  5109.8 2097.27  5129.8 2097.97  5139.8 2098.97  5179.8 2100.17
#Mann=4,-1,0
  4498.8   0.035       0  4683.5    0.07       0  4994.1    0.07       0
  5000.0    0.07       0
Bank Sta=4994.1,5000
Exp/Cntr=0.3,0.1

Type RM Length L Ch R = 1,1252,157,157,157
BEGIN DESCRIPTION:
Sweetwater Creek Trib 27 T6 4006
END DESCRIPTION:
XS GIS Cut Line= 3
      1379497.30      6878967.17      1379338.36      6878971.32
      1379195.48      6879153.72
#Sta/Elev= 30
  4841.0 2097.23  4853.3 2097.41  4883.3 2095.83  4913.3 2088.71  4933.3 2085.12
  4943.3 2084.11  4963.3 2083.69  4983.4 2083.70  4993.4 2083.89  4999.2 2084.69
  5007.8 2084.04  5014.2 2084.21  5021.2 2082.83  5028.7 2082.42  5040.1 2082.26
  5040.6 2081.76  5045.6 2081.76  5046.1 2082.26  5063.9 2082.90  5072.0 2082.82
  5084.7 2084.15  5092.8 2085.42  5099.2 2087.31  5107.3 2089.08  5113.7 2090.93
  5121.8 2092.53  5135.5 2095.70  5148.9 2095.74  5171.5 2096.61  5231.7 2096.45
#Mann=3,-1,0
  4841.0    0.07       0  5040.1    0.07       0  5046.1    0.07       0
Bank Sta=5040.1,5046.1
Exp/Cntr=0.3,0.1

Type RM Length L Ch R = 1,1095,354,354,354
BEGIN DESCRIPTION:
Sweetwater Creek Trib 27 T6 4005
END DESCRIPTION:
XS GIS Cut Line= 3
      1379369.28      6878817.52      1379226.82      6878859.81
      1379090.95      6879074.41
#Sta/Elev= 30
  4851.4 2091.82  4865.9 2091.57  4871.1 2092.22  4876.7 2091.66  4904.3 2092.00
  4928.9 2089.73  4937.5 2090.05  4942.7 2090.75  4960.2 2090.20  4975.9 2088.90
  4981.2 2087.20  4991.5 2085.09  4998.3 2082.89  5005.3 2081.69  5005.8 2081.19
  5010.8 2081.19  5011.3 2081.69  5014.2 2083.21  5021.5 2085.40  5035.4 2087.33
  5065.9 2089.29  5080.7 2091.36  5093.0 2093.84  5102.3 2094.25  5108.3 2093.83
  5123.5 2094.55  5129.4 2093.19  5151.7 2093.33  5238.8 2095.68  5254.0 2095.63
#Mann=3,-1,0
  4851.4    0.07       0  5005.3    0.07       0  5011.3    0.07       0
Bank Sta=5005.3,5011.3
Exp/Cntr=0.3,0.1

Type RM Length L Ch R = 1,741,0,0,0
BEGIN DESCRIPTION:
Sweetwater Creek Trib 27 T6 1271
END DESCRIPTION:
XS GIS Cut Line= 3
      1379405.43      6878872.76      1379065.28      6878577.84
      1378828.40      6878725.83
#Sta/Elev= 30
  4549.8 2094.41  4603.3 2091.93  4610.2 2092.70  4638.7 2091.30  4696.0 2091.19
  4737.5 2091.50  4787.8 2089.64  4794.5 2087.95  4808.7 2088.90  4815.3 2087.75
  4829.6 2087.61  4900.8 2088.27  4915.1 2084.80  4918.1 2085.08  4935.9 2084.79
  4943.6 2083.65  4950.2 2084.98  4957.8 2084.67  4972.1 2086.36  5008.0 2085.85
  5029.2 2083.89  5041.5 2080.91  5042.0 2080.41  5047.5 2080.91  5059.3 2082.96
  5065.8 2087.88  5071.7 2089.22  5146.0 2089.20  5189.0 2088.59  5279.3 2090.27
#Mann=6,-1,0
  4549.8    0.07       0  4696.0   0.035       0  4918.1    0.07       0
  5041.5    0.07       0  5047.5    0.07       0  5146.0   0.035       0
Bank Sta=5041.5,5047.5
Exp/Cntr=0.3,0.1

Chan Stop Cuts=-1