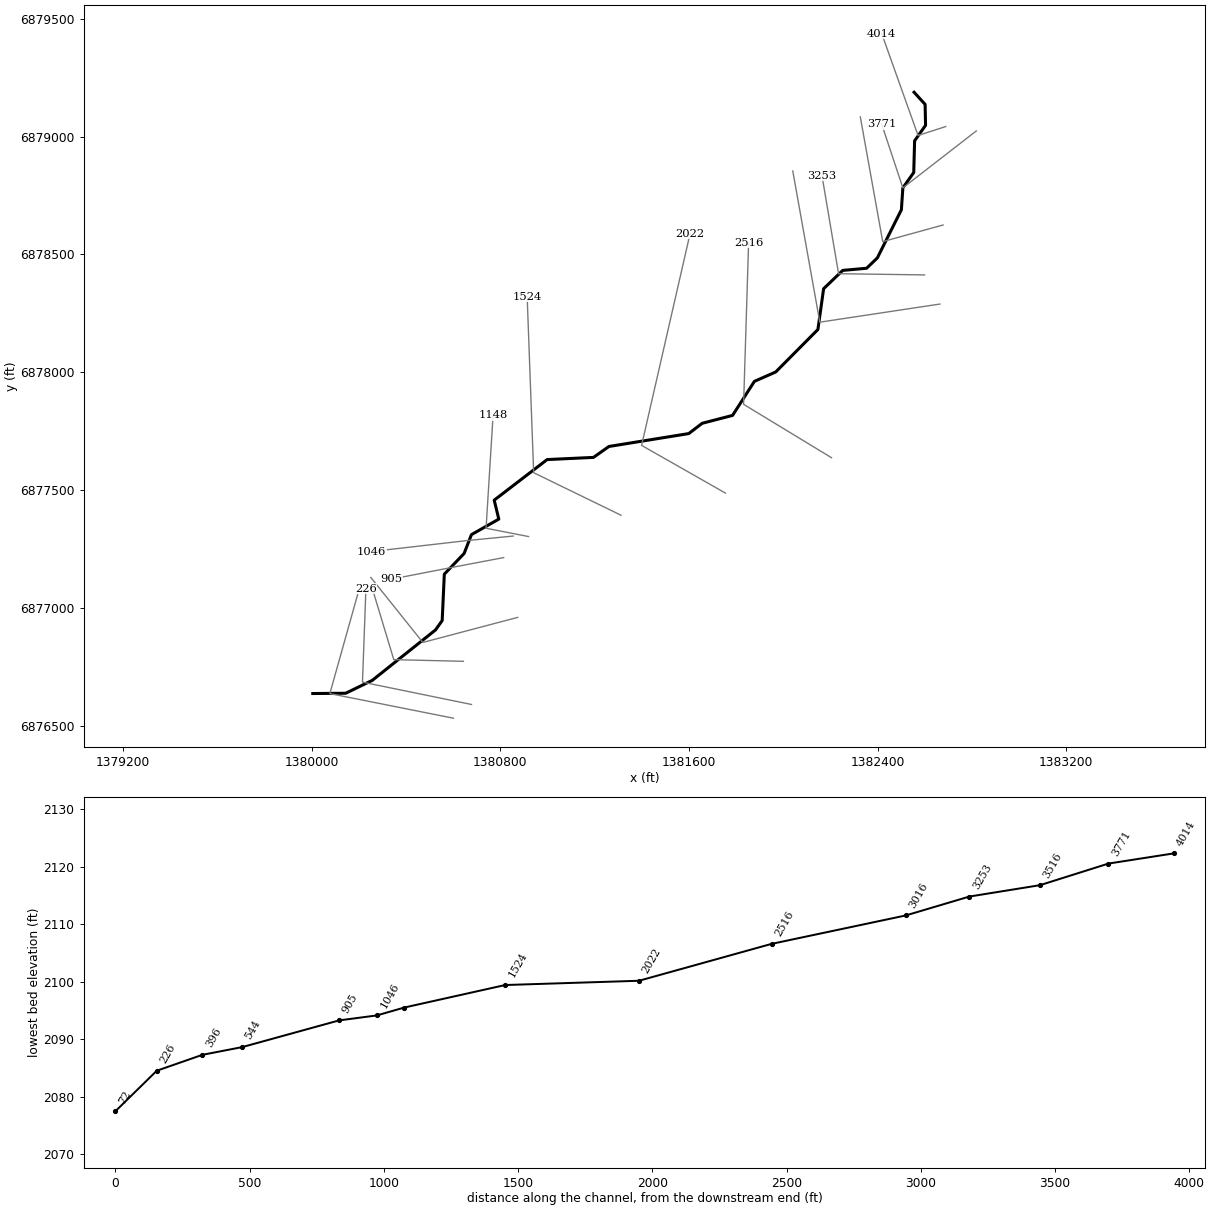
--- Sweetwater Creek Trib 27 T7.prj (project) ---

Proj Title=Sweetwater Creek Trib 27 T7 Base Level Engineering
Current Plan=p01
Default Exp/Contr=0.3,0.1
English Units
Geom File=g01
Flow File=f01
Plan File=p01
Y Axis Title=Elevation
X Axis Title(PF)=Main Channel Distance
X Axis Title(XS)=Station
BEGIN DESCRIPTION:
Sweetwater Creek Trib 27 T7
END DESCRIPTION:
DSS Export Rating Curves= 0
DSS Export Rating Curve Sorted= 0
DSS Export Volume Flow Curves= 0
DXF OffsetX= 0
DXF OffsetY= 0
DXF ScaleX= 1
DXF ScaleY= 10

--- Sweetwater Creek Trib 27 T7.p01 (plan) ---

Plan Title=Multiple Run
Short Identifier=Multiple
Geom File=g01
Flow File=f01
Subcritical Flow
K Sum by GR= 0
Std Step Tol= 0.01
Critical Tol= 0.01
Num of Std Step Trials= 20
Max Error Tol= 0.3
Flow Tol Ratio= 0.001
Split Flow NTrial= 30
Split Flow Tol= 0.02
Split Flow Ratio= 0.02
Log Output Level= 0
Friction Slope Method= 1
Unsteady Friction Slope Method= 2
Unsteady Bridges Friction Slope Method= 1
Parabolic Critical Depth
Global Vel Dist=  1 , 1 , 1
Global Log Level= 0
CheckData=True
Encroach Param= -1, 0, 0, 0
BEGIN DESCRIPTION:
Multiple Run
END DESCRIPTION:

--- Sweetwater Creek Trib 27 T7.f01 (steady flow) ---

Flow Title=Multiple
Program Version=4.10
Number of Profiles= 7
Profile Names=10-year,25-year,50-year,1pct_min,100-year,1pct_plu,500-year
River Rch & RM=Sweetwater Creek,Reach-1         ,4014
     176     243     298     182     363     725     546
Boundary for River Rch & Prof#=Sweetwater Creek,Reach-1         , 1
Up Type= 0
Dn Type= 3
Dn Slope=0.005
Boundary for River Rch & Prof#=Sweetwater Creek,Reach-1         , 2
Up Type= 0
Dn Type= 3
Dn Slope=0.005
Boundary for River Rch & Prof#=Sweetwater Creek,Reach-1         , 3
Up Type= 0
Dn Type= 3
Dn Slope=0.005
Boundary for River Rch & Prof#=Sweetwater Creek,Reach-1         , 4
Up Type= 0
Dn Type= 3
Dn Slope=0.005
Boundary for River Rch & Prof#=Sweetwater Creek,Reach-1         , 5
Up Type= 0
Dn Type= 3
Dn Slope=0.005
Boundary for River Rch & Prof#=Sweetwater Creek,Reach-1         , 6
Up Type= 0
Dn Type= 3
Dn Slope=0.005
Boundary for River Rch & Prof#=Sweetwater Creek,Reach-1         , 7
Up Type= 0
Dn Type= 3
Dn Slope=0.005
DSS Import GetInterval= 0
DSS Import GetPeak= 0
DSS Import FillOption= 0

--- Sweetwater Creek Trib 27 T7.g01 (geometry) ---

Geom Title=Existing Conditions
Program Version=4.10

River Reach=Sweetwater Creek,Reach-1
Reach XY= 30
        1382555.        6879188.      1382601.81       6879136.6
      1382603.74      6879047.69      1382557.27      6878982.06
      1382553.61      6878847.67      1382507.47      6878782.43
      1382501.17      6878689.58      1382399.28      6878485.42
      1382353.72      6878441.53      1382252.56      6878432.48
      1382171.42       6878354.8      1382147.18      6878181.81
       1381968.2      6878001.64      1381877.86      6877961.84
      1381785.27      6877817.49       1381656.6      6877784.14
      1381599.47      6877740.39      1381260.94      6877685.73
      1381195.34      6877639.38      1380998.81      6877630.17
      1380774.36      6877458.04      1380793.89      6877377.68
      1380677.87      6877311.84      1380646.81      6877231.98
      1380562.83      6877144.19       1380553.8      6876947.58
      1380525.52      6876907.72       1380257.3      6876693.83
      1380144.52      6876639.15        1380005.        6876638.

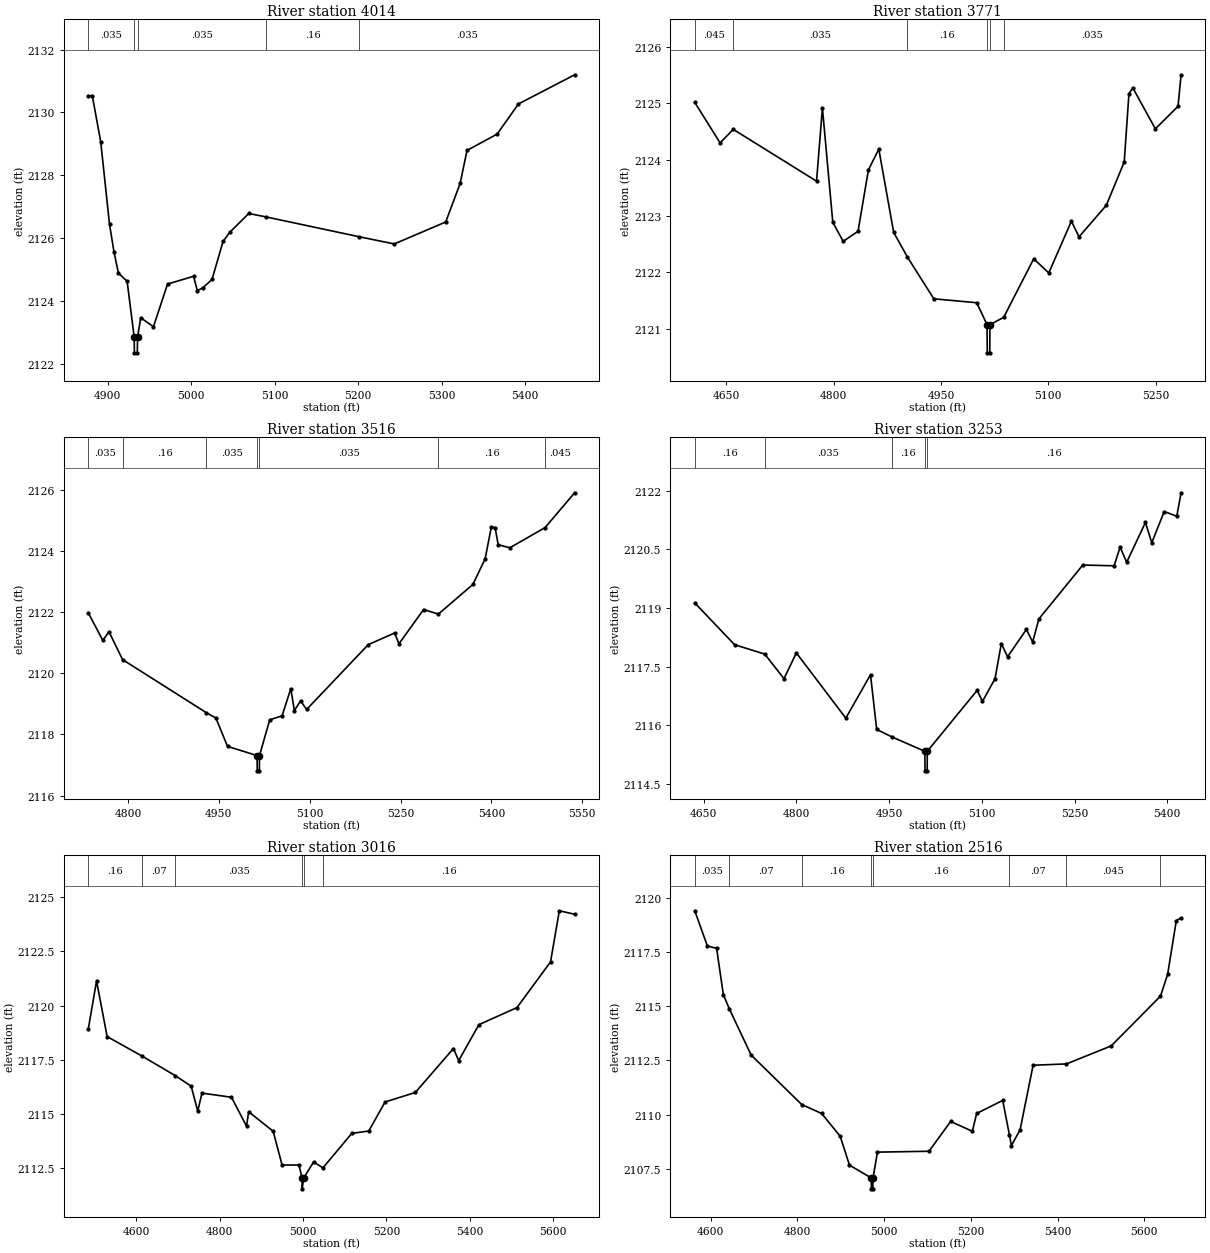
Type RM Length L Ch R = 1 ,4014    ,243,243,243
BEGIN DESCRIPTION:
Sweetwater Creek Trib 27 T7 7.0
END DESCRIPTION:
XS GIS Cut Line= 3
      1382689.21      6879042.53       1382571.9      6879004.58
      1382417.65       6879437.1
#Sta/Elev= 30
  4876.7 2130.53  4881.5 2130.53  4891.6 2129.06  4902.1 2126.44  4907.5 2125.55
  4912.8 2124.88  4923.2 2124.62  4931.7 2122.84  4931.9 2122.34  4935.4 2122.34
  4935.7 2122.84  4939.5 2123.46  4954.7 2123.17  4971.6 2124.53  5002.8 2124.78
  5007.3 2124.32  5014.3 2124.42  5024.9 2124.68  5038.1 2125.89  5046.1 2126.18
  5068.9 2126.78  5089.8 2126.67    5201 2126.04  5243.2 2125.81  5304.8 2126.51
  5322.1 2127.74  5330.3 2128.79  5366.4 2129.31  5391.9 2130.27  5459.2  2131.2
#Mann= 5 ,-1 , 0
  4876.7    .035       0  4931.7    .035       0  4935.7    .035       0
  5089.8     .16       0    5201    .035       0
Bank Sta=4931.7,4935.7
XS Rating Curve= 0 ,0
Exp/Cntr=0.3,0.1

Type RM Length L Ch R = 1 ,3771    ,255,255,255
BEGIN DESCRIPTION:
Sweetwater Creek Trib 27 T7 6.1
END DESCRIPTION:
XS GIS Cut Line= 3
       1382818.9      6879023.93      1382507.47      6878782.43
      1382417.44      6879053.47
#Sta/Elev= 30
  4605.9 2125.02  4641.3  2124.3  4659.7 2124.54  4776.1 2123.62  4784.3 2124.92
  4798.8 2122.89  4813.3 2122.55  4834.1 2122.73  4848.6 2123.82  4863.1 2124.19
  4883.9 2122.71  4903.2 2122.27    4940 2121.53    5000 2121.46  5014.4 2121.07
  5014.7 2120.57  5018.2 2120.57  5018.4 2121.07  5037.6  2121.2  5079.6 2122.24
  5100.7 2121.99  5132.3 2122.91  5142.9 2122.63    5181 2123.19  5206.1 2123.96
  5212.7 2125.17    5218 2125.28  5249.6 2124.55  5281.3 2124.95  5285.6 2125.51
#Mann= 6 ,-1 , 0
  4605.9    .045       0  4659.7    .035       0  4903.2     .16       0
  5014.4     .07       0  5018.4     .16       0  5037.6    .035       0
Bank Sta=5014.4,5018.4
XS Rating Curve= 0 ,0
Exp/Cntr=0.3,0.1

Type RM Length L Ch R = 1 ,3516    ,263,263,263
BEGIN DESCRIPTION:
Sweetwater Creek Trib 27 T7 6.0
END DESCRIPTION:
XS GIS Cut Line= 3
        1382678.        6878625.      1382422.03      6878554.51
      1382326.99      6879083.33
#Sta/Elev= 30
  4734.5 2121.98  4758.4 2121.08  4768.7 2121.36  4791.1 2120.45  4929.6 2118.71
  4945.1 2118.54  4964.3 2117.61  5013.1 2117.31  5013.4 2116.81  5016.9 2116.81
  5017.1 2117.31    5034 2118.48  5054.4 2118.61  5068.8  2119.5  5074.7 2118.78
  5084.8  2119.1    5095 2118.82  5196.6 2120.94    5240 2121.32  5247.4 2120.97
    5288 2122.09  5312.4 2121.94  5369.3 2122.91  5389.6 2123.75  5399.8 2124.79
    5406 2124.77  5411.1 2124.21  5430.3 2124.11  5488.5 2124.77  5537.3 2125.91
#Mann= 7 ,-1 , 0
  4734.5    .035       0  4791.1     .16       0  4929.6    .035       0
  5013.1    .035       0  5017.1    .035       0  5312.4     .16       0
  5488.5    .045       0
Bank Sta=5013.1,5017.1
XS Rating Curve= 0 ,0
Exp/Cntr=0.3,0.1

Type RM Length L Ch R = 1 ,3253    ,237,237,237
BEGIN DESCRIPTION:
Sweetwater Creek Trib 27 T7 5.1
END DESCRIPTION:
XS GIS Cut Line= 3
      1382599.37      6878413.36       1382234.8      6878418.39
      1382164.31      6878834.87
#Sta/Elev= 30
  4635.4 2119.13  4699.8 2118.06  4748.6 2117.82  4779.8 2117.19  4799.8 2117.85
  4879.8 2116.18  4919.8 2117.29  4929.8 2115.89  4954.3  2115.7  5007.7 2115.33
    5008 2114.83  5011.5 2114.83  5011.7 2115.33  5092.3 2116.89    5101 2116.61
  5121.3 2117.19  5131.5 2118.09  5141.6 2117.75    5172 2118.45  5182.2 2118.13
  5192.3 2118.72  5263.3  2120.1    5314 2120.08  5323.7 2120.56  5334.3 2120.17
  5364.7 2121.19  5374.9 2120.67  5395.1 2121.47  5415.4 2121.35  5422.4 2121.95
#Mann= 5 ,-1 , 0
  4635.4     .16       0  4748.6    .035       0  4954.3     .16       0
  5007.7     .07       0  5011.7     .16       0
Bank Sta=5007.7,5011.7
XS Rating Curve= 0 ,0
Exp/Cntr=0.3,0.1

Type RM Length L Ch R = 1 ,3016    ,500,500,500
BEGIN DESCRIPTION:
Sweetwater Creek Trib 27 T7 5.0
END DESCRIPTION:
XS GIS Cut Line= 3
       1382664.6      6878289.75      1382155.27      6878212.89
      1382040.56      6878854.11
#Sta/Elev= 30
  4484.9 2118.92  4504.7 2121.14  4530.1 2118.57    4613 2117.68  4693.3 2116.77
  4731.7 2116.28  4747.4 2115.13  4757.6 2115.96  4828.3 2115.77  4864.5 2114.43
  4869.5  2115.1  4928.3  2114.2  4949.7 2112.64  4990.2 2112.64  4997.6 2112.04
  4997.9 2111.54  5001.6 2112.04  5025.2 2112.78  5047.7 2112.51  5116.9  2114.1
  5157.6 2114.21  5196.7 2115.55  5269.3 2115.99  5360.7 2118.02  5373.3 2117.46
  5421.7 2119.12  5513.1 2119.91  5593.6 2122.02  5614.7 2124.38  5651.4 2124.22
#Mann= 6 ,-1 , 0
  4484.9     .16       0    4613     .07       0  4693.3    .035       0
  4997.6    .035       0  5001.6    .035       0  5047.7     .16       0
Bank Sta=4997.6,5001.6
XS Rating Curve= 0 ,0
Exp/Cntr=0.3,0.1

Type RM Length L Ch R = 1 ,2516    ,494,494,494
BEGIN DESCRIPTION:
Sweetwater Creek Trib 27 T7 4.0
END DESCRIPTION:
XS GIS Cut Line= 3
      1382205.02      6877637.99        1381832.      6877864.49
      1381853.29      6878549.06
#Sta/Elev= 30
  4563.6 2119.39  4592.7 2117.77    4614 2117.66  4629.5 2115.53  4643.2 2114.88
  4693.5 2112.75  4810.3 2110.47  4856.1 2110.06  4898.9 2109.01  4920.3 2107.68
  4970.6 2107.09  4970.8 2106.59  4974.3 2106.59  4974.6 2107.09  4984.8 2108.28
  5103.6 2108.32  5153.6 2109.69  5203.6 2109.24  5213.6 2110.06  5273.6 2110.66
  5289.1 2109.07  5293.7 2108.58  5313.7 2109.31  5343.7 2112.28  5420.5 2112.34
  5523.8 2113.17  5637.4 2115.46  5653.8 2116.46  5673.8 2118.93  5684.9 2119.07
#Mann= 8 ,-1 , 0
  4563.6    .035       0  4643.2     .07       0  4810.3     .16       0
  4970.6     .07       0  4974.6     .16       0  5289.1     .07       0
  5420.5    .045       0  5637.4     .07       0
Bank Sta=4970.6,4974.6
XS Rating Curve= 0 ,0
Exp/Cntr=0.3,0.1

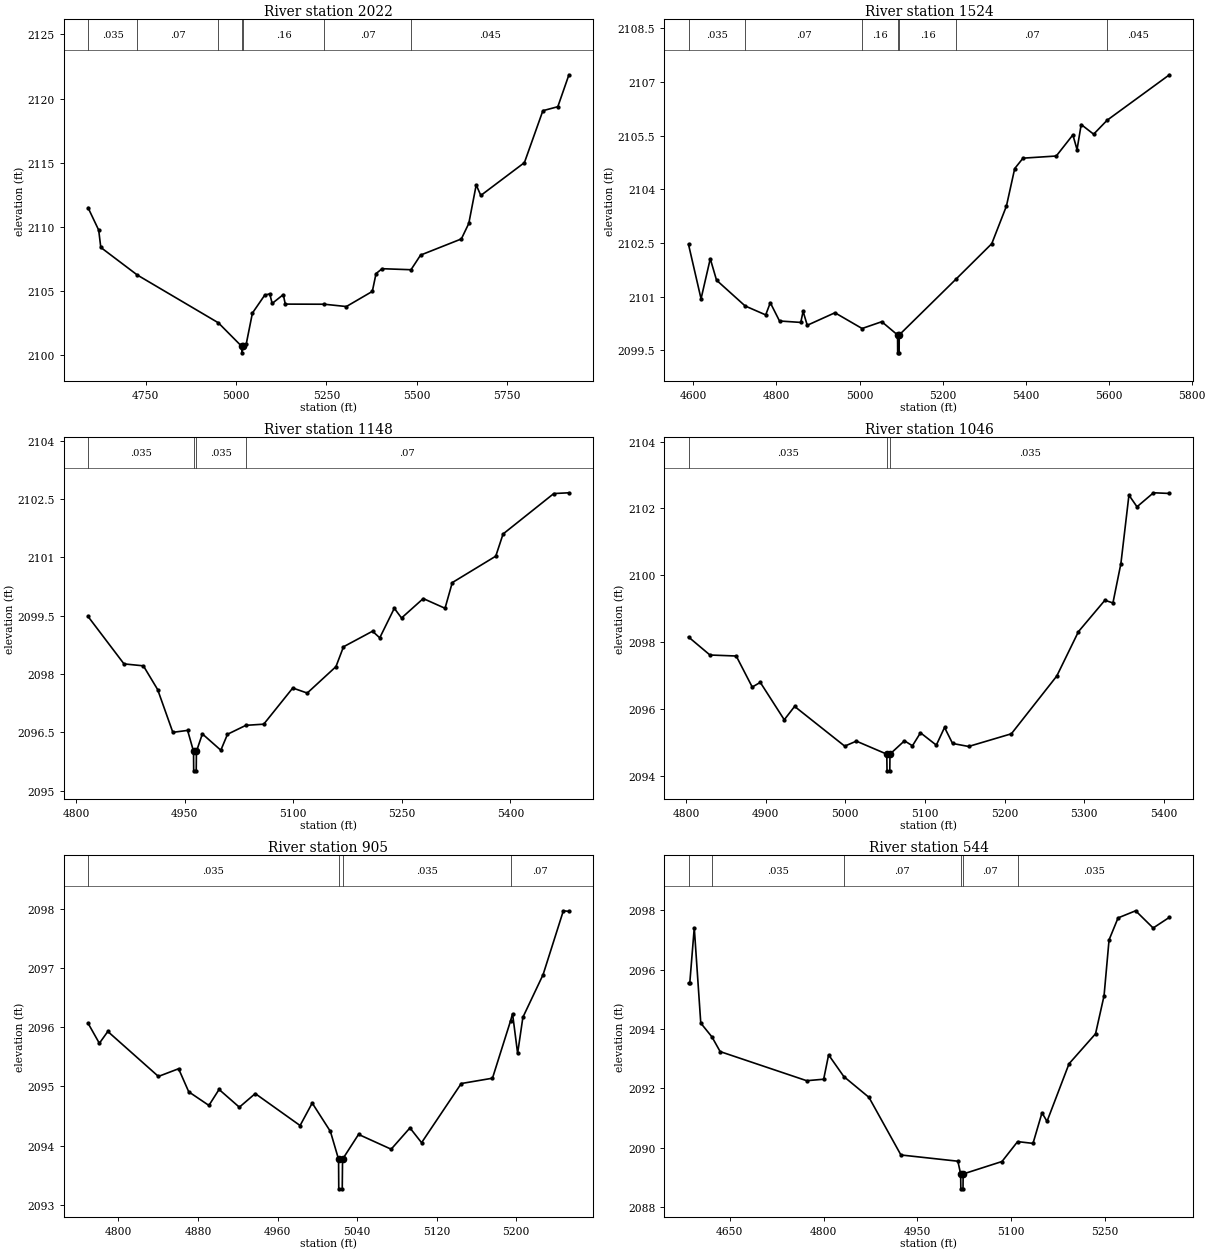
Type RM Length L Ch R = 1 ,2022    ,498,498,498
BEGIN DESCRIPTION:
Sweetwater Creek Trib 27 T7 3.0
END DESCRIPTION:
XS GIS Cut Line= 3
        1381755.        6877488.      1381399.47      6877690.39
      1381604.99      6878587.96
#Sta/Elev= 30
  4590.9 2111.49  4620.4 2109.74  4626.2 2108.39  4727.1 2106.24  4951.4 2102.51
  5016.1 2100.67  5016.3 2100.17  5020.1 2100.67  5028.3 2100.84  5045.5 2103.27
  5079.6 2104.67  5093.5 2104.77  5100.1 2104.02  5130.9 2104.71  5136.4 2103.97
  5244.4 2103.96  5305.3 2103.78  5377.1 2104.96  5387.4 2106.35  5404.2 2106.73
  5484.1 2106.65  5510.5 2107.79  5623.3 2109.05  5643.9 2110.26  5664.4 2113.26
  5677.1 2112.44  5797.7    2115  5848.8 2119.05  5890.1 2119.36  5920.8 2121.85
#Mann= 7 ,-1 , 0
  4590.9    .035       0  4727.1     .07       0  4951.4     .16       0
  5016.1     .07       0  5020.1     .16       0  5244.4     .07       0
  5484.1    .045       0
Bank Sta=5016.1,5020.1
XS Rating Curve= 0 ,0
Exp/Cntr=0.3,0.1

Type RM Length L Ch R = 1 ,1524    ,376,376,376
BEGIN DESCRIPTION:
Sweetwater Creek Trib 27 T7 2.0
END DESCRIPTION:
XS GIS Cut Line= 3
      1381312.13      6877394.18      1380941.76      6877574.44
      1380914.18      6878320.33
#Sta/Elev= 30
  4588.1 2102.46  4618.3 2100.94  4640.5 2102.06  4655.6 2101.46  4724.5 2100.74
    4774 2100.49  4785.1 2100.83  4807.3 2100.32  4858.5 2100.28  4864.1 2100.59
  4874.1  2100.2  4940.8 2100.55  5006.2 2100.11  5053.6  2100.3  5091.6 2099.93
  5091.9 2099.43  5095.4 2099.43  5095.6 2099.93  5232.4 2101.49  5318.5 2102.48
  5353.8 2103.53  5373.8 2104.58  5393.8 2104.87  5473.9 2104.93  5513.9 2105.52
  5523.9 2105.11  5533.9 2105.81  5563.9 2105.54  5596.4 2105.93  5746.4  2107.2
#Mann= 7 ,-1 , 0
  4588.1    .035       0  4724.5     .07       0  5006.2     .16       0
  5091.6     .07       0  5095.6     .16       0  5232.4     .07       0
  5596.4    .045       0
Bank Sta=5091.6,5095.6
XS Rating Curve= 0 ,0
Exp/Cntr=0.3,0.1

Type RM Length L Ch R = 1 ,1148    ,102,102,102
BEGIN DESCRIPTION:
Sweetwater Creek Trib 27 T7 1.0
END DESCRIPTION:
XS GIS Cut Line= 3
      1380920.06      6877303.75      1380739.85       6877338.9
      1380769.69      6877818.87
#Sta/Elev= 30
  4816.4 2099.48  4866.1 2098.26  4892.9 2098.21  4912.6  2097.6  4933.6  2096.5
    4954 2096.55  4962.2 2096.01  4962.4 2095.51  4965.9 2095.51  4966.2 2096.01
  4974.4 2096.46  4999.9 2096.04  5009.1 2096.45  5034.5 2096.68  5059.2 2096.71
  5099.3 2097.64  5119.3 2097.51    5159 2098.19  5169.4  2098.7  5209.5  2099.1
  5219.5 2098.93  5239.6 2099.69  5249.6 2099.44  5279.6 2099.94  5309.7 2099.69
  5319.7 2100.35  5379.8 2101.03  5389.9  2101.6    5460 2102.64  5480.9 2102.66
#Mann= 4 ,-1 , 0
  4816.4    .035       0  4962.2    .035       0  4966.2    .035       0
  5034.5     .07       0
Bank Sta=4962.2,4966.2
XS Rating Curve= 0 ,0
Exp/Cntr=0.3,0.1

Type RM Length L Ch R = 1 ,1046    ,141,141,141
BEGIN DESCRIPTION:
Sweetwater Creek Trib 27 T7 4002
END DESCRIPTION:
XS GIS Cut Line= 3
      1380854.64      6877305.85      1380658.89      6877286.57
      1380254.54      6877240.23
#Sta/Elev= 30
  4803.3 2098.15  4830.2 2097.61  4863.2 2097.58  4883.3 2096.65  4893.4 2096.79
  4923.5 2095.67  4936.5 2096.07  4999.4 2094.88    5014 2095.03  5052.2 2094.64
  5052.5 2094.14    5056 2094.14  5056.2 2094.64  5074.4 2095.04  5084.4 2094.89
  5094.5 2095.28  5114.4 2094.91  5124.7 2095.44  5134.8 2094.96  5154.9 2094.87
  5208.6 2095.25  5265.6 2096.98  5292.8 2098.31    5326 2099.25  5336.1 2099.17
  5346.1 2100.35  5356.2  2102.4  5366.3 2102.05    5387 2102.47    5407 2102.45
#Mann= 3 ,-1 , 0
  4803.3    .035       0  5052.2    .035       0  5056.2    .035       0
Bank Sta=5052.2,5056.2
XS Rating Curve= 0 ,0
Exp/Cntr=0.3,0.1

Type RM Length L Ch R = 1 ,905     ,361,361,361
BEGIN DESCRIPTION:
Sweetwater Creek Trib 27 T7 4003
END DESCRIPTION:
XS GIS Cut Line= 3
      1380814.52      6877214.48      1380587.96      6877171.49
      1380339.53       6877123.1
#Sta/Elev= 30
  4769.4 2096.07  4780.8 2095.73  4789.3 2095.93  4840.2 2095.17  4860.5  2095.3
  4870.7 2094.91    4891 2094.68  4901.2 2094.95  4921.6 2094.65  4937.6 2094.88
  4982.7 2094.34  4994.9 2094.72  5013.2 2094.24  5021.4 2093.77  5021.6 2093.27
  5025.1 2093.27  5025.4 2093.77  5041.5 2094.19  5074.3 2093.94  5093.2  2094.3
  5104.9 2094.05  5144.8 2095.05  5176.2 2095.14  5194.4 2096.11  5196.4 2096.23
  5201.5 2095.56  5206.8 2096.17  5227.1 2096.89  5247.5 2097.97  5253.1 2097.96
#Mann= 4 ,-1 , 0
  4769.4    .035       0  5021.4    .035       0  5025.4    .035       0
  5194.4     .07       0
Bank Sta=5021.4,5025.4
XS Rating Curve= 0 ,0
Exp/Cntr=0.3,0.1

Type RM Length L Ch R = 1 ,544     ,148,148,148
BEGIN DESCRIPTION:
Sweetwater Creek Trib 27 T7 2885
END DESCRIPTION:
XS GIS Cut Line= 3
      1380873.91      6876960.89      1380471.71      6876854.64
      1380251.24       6877130.2
#Sta/Elev= 30
    4584 2095.54    4586 2095.54  4593.2 2097.41  4603.6  2094.2  4621.6 2093.73
  4634.6 2093.24  4772.9 2092.26  4800.1 2092.31    4808 2093.13  4832.3  2092.4
  4872.5  2091.7  4923.6 2089.76  5014.7 2089.55  5019.1 2089.12  5019.4 2088.62
  5022.9 2088.62  5023.1 2089.12  5085.2 2089.54  5110.2 2090.21  5134.8 2090.15
  5149.2 2091.18  5157.2 2090.89  5192.4 2092.83  5234.8 2093.84  5248.4 2095.12
  5256.4    2097  5270.8 2097.74  5298.9 2097.98  5326.9  2097.4  5352.9 2097.76
#Mann= 6 ,-1 , 0
    4584     .07       0  4621.6    .035       0  4832.3     .07       0
  5019.1     .07       0  5023.1     .07       0  5110.2    .035       0
Bank Sta=5019.1,5023.1
XS Rating Curve= 0 ,0
Exp/Cntr=0.3,0.1

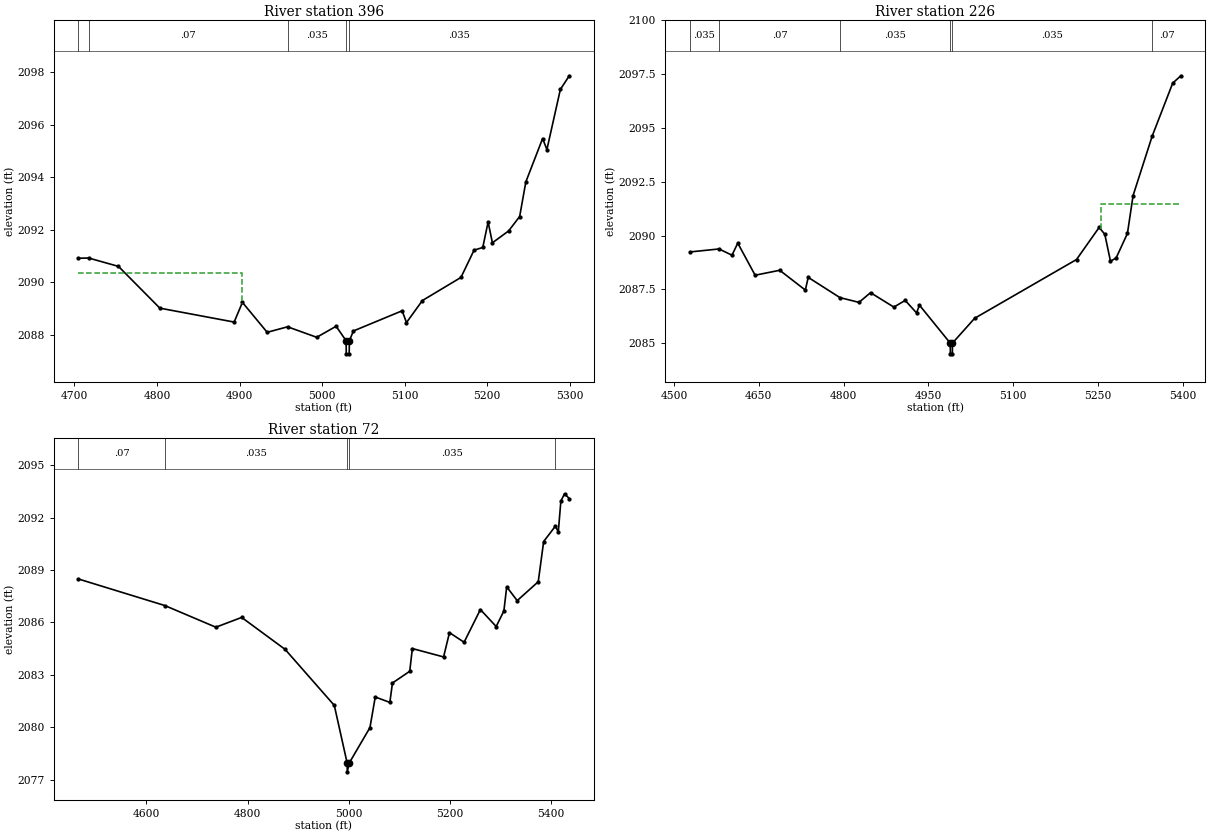
Type RM Length L Ch R = 1 ,396     ,170,170,170
BEGIN DESCRIPTION:
Sweetwater Creek Trib 27 T7 4394
END DESCRIPTION:
XS GIS Cut Line= 3
      1380643.73      6876774.62      1380348.52      6876781.73
      1380261.98      6877068.35
#Sta/Elev= 30
  4704.7 2090.92  4717.2 2090.93  4753.4 2090.61  4803.5 2089.02  4893.5 2088.49
  4903.5 2089.24  4933.5  2088.1  4958.2 2088.31  4993.5 2087.91    5017 2088.33
  5029.1 2087.78  5029.3 2087.28  5032.8 2087.28  5033.1 2087.78  5037.9 2088.15
    5097 2088.92  5102.2 2088.47  5121.5 2089.31  5168.2 2090.19  5184.1 2091.23
  5194.6 2091.33  5201.1  2092.3  5206.3 2091.51  5225.9 2091.96  5239.3 2092.51
  5246.8 2093.83  5267.1 2095.48  5272.3 2095.06  5288.6 2097.35  5299.4 2097.87
#Mann= 5 ,-1 , 0
  4704.7    .035       0  4717.2     .07       0  4958.2    .035       0
  5029.1    .035       0  5033.1    .035       0
#XS Ineff= 2 , 0
         4902.84 2090.35
Permanent Ineff=
       F       F
Bank Sta=5029.1,5033.1
XS Rating Curve= 0 ,0
Exp/Cntr=0.3,0.1

Type RM Length L Ch R = 1 ,226     ,154,154,154
BEGIN DESCRIPTION:
Sweetwater Creek Trib 27 T7 4118
END DESCRIPTION:
XS GIS Cut Line= 3
      1380678.02       6876591.6      1380215.71      6876686.28
      1380230.32      6877082.41
#Sta/Elev= 30
  4528.1 2089.24  4579.6 2089.38  4602.6 2089.09  4612.8 2089.65  4643.5 2088.16
    4687 2088.39  4732.3 2087.47  4737.4 2088.06  4793.5 2087.12  4827.2  2086.9
  4847.6 2087.35  4888.8 2086.68  4908.9 2086.99    4929 2086.41  4934.1 2086.77
  4988.5 2085.01  4988.8 2084.51  4992.3 2084.51  4992.5 2085.01  5031.7 2086.16
  5211.9 2088.89  5251.9 2090.38  5261.9 2090.06  5271.9 2088.81  5281.9 2088.96
  5301.9  2090.1  5311.9 2091.86  5345.7 2094.62    5382 2097.08  5396.4 2097.42
#Mann= 6 ,-1 , 0
  4528.1    .035       0  4579.6     .07       0  4793.5    .035       0
  4988.5    .035       0  4992.5    .035       0  5345.7     .07       0
#XS Ineff= 2 , 0
                         5254.82         2091.49
Permanent Ineff=
       F       F
Bank Sta=4988.5,4992.5
XS Rating Curve= 0 ,0
Exp/Cntr=0.3,0.1

Type RM Length L Ch R = 1 ,72      ,0,0,0
BEGIN DESCRIPTION:
Sweetwater Creek Trib 27 T7 4119
END DESCRIPTION:
XS GIS Cut Line= 3
      1380601.58      6876533.33      1380077.38      6876637.72
        1380195.      6877057.03
#Sta/Elev= 30
  4465.5 2088.49  4636.4 2086.97  4737.3 2085.73  4788.3 2086.29  4874.2 2084.46
  4971.3 2081.26  4996.7 2077.96  4996.9 2077.46  5000.7 2077.96  5041.7 2079.99
  5052.2 2081.74    5081 2081.43  5086.2 2082.54  5120.3 2083.21  5125.5 2084.51
  5187.2 2084.03  5198.8 2085.42  5227.7 2084.87  5259.9 2086.74  5291.1 2085.77
  5306.3 2086.66  5311.9 2088.04  5332.6 2087.25  5374.2 2088.33  5384.9 2090.63
  5408.1 2091.51  5413.8 2091.18  5418.9 2092.94  5426.1 2093.36  5435.5 2093.09
#Mann= 5 ,-1 , 0
  4465.5     .07       0  4636.4    .035       0  4996.7    .035       0
  5000.7    .035       0  5408.1     .07       0
Bank Sta=4996.7,5000.7
XS Rating Curve= 0 ,0
Exp/Cntr=0.3,0.1

Chan Stop Cuts=-1
Use User Specified Reach Order=0
Composite Channel Slope=5