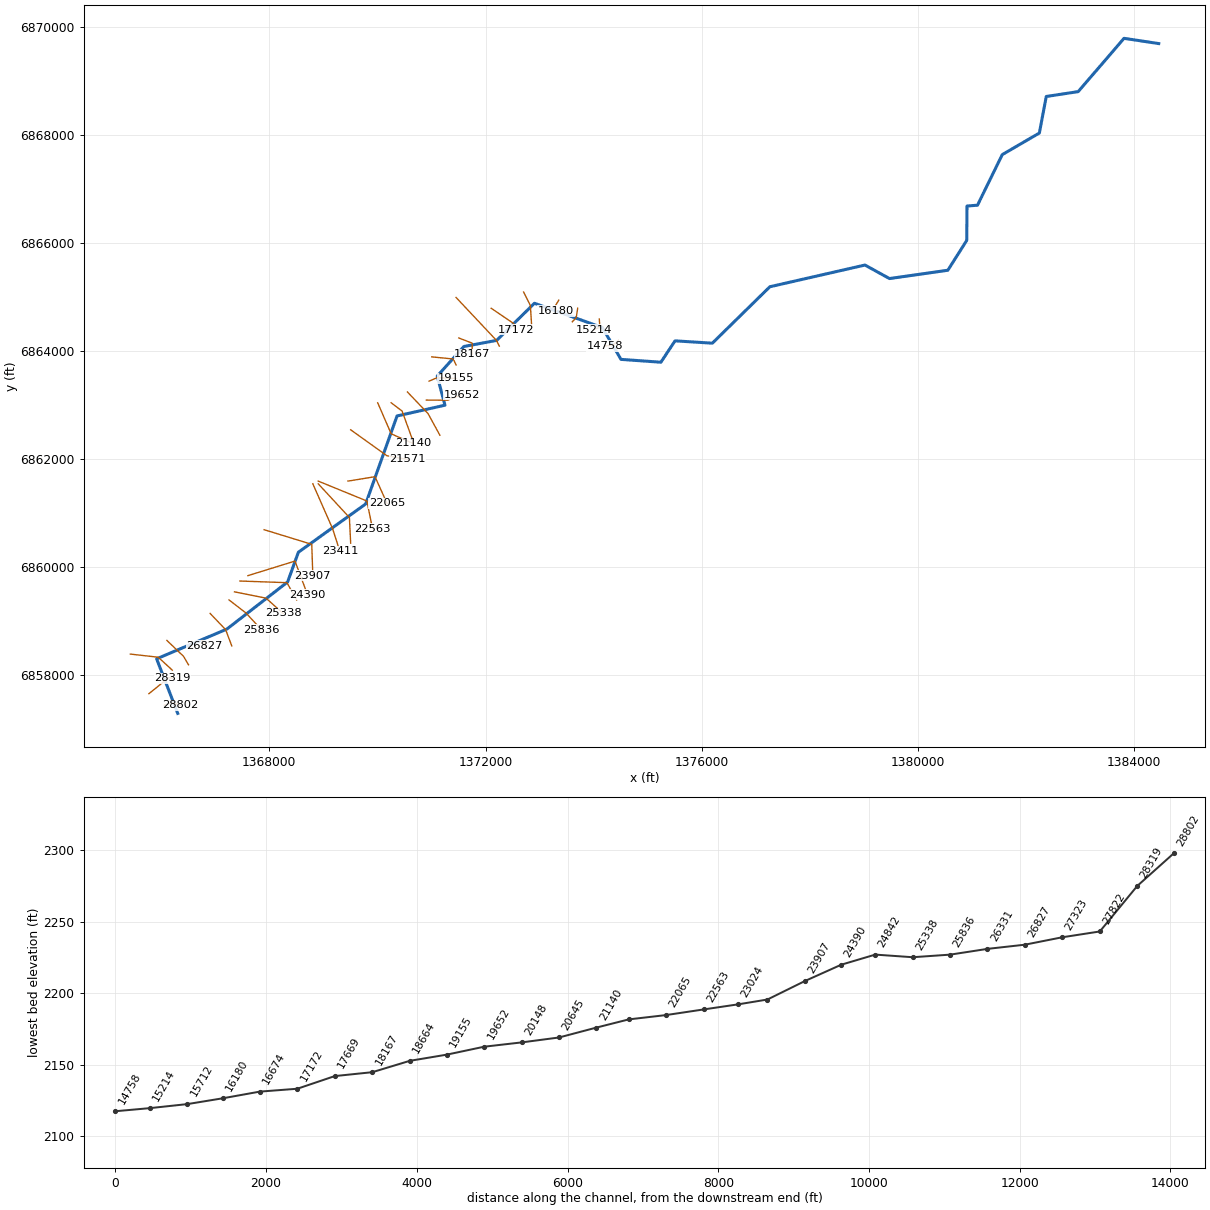
--- Sweetwater Creek Trib 27 T8.prj (project) ---

Proj Title=Sweetwater Creek Trib 27 T8 Base Level Engineering
Current Plan=p01
Default Exp/Contr=0.3,0.1
English Units
Geom File=g01
Flow File=f01
Plan File=p01
BEGIN DESCRIPTION:
Sweetwater Creek Trib 27 T8
END DESCRIPTION:

--- Sweetwater Creek Trib 27 T8.p01 (plan) ---

Plan Title=Multiple Run
Short Identifier=Multiple
Geom File=g01
Flow File=f01
Subcritical Flow
K Sum by GR= 0
Std Step Tol= 0.01
Critical Tol= 0.01
Num of Std Step Trials= 20
Max Error Tol= 0.3
Flow Tol Ratio= 0.001
Split Flow NTrial= 30
Split Flow Tol= 0.02
Split Flow Ratio= 0.02
Log Output Level= 0
Friction Slope Method= 1
Unsteady Friction Slope Method= 2
Unsteady Bridges Friction Slope Method= 1
Parabolic Critical Depth
Global Vel Dist=  1 , 1 , 1
Global Log Level= 0
CheckData=True
Encroach Param= -1, 0, 0, 0
BEGIN DESCRIPTION:
Multiple Run
END DESCRIPTION:

--- Sweetwater Creek Trib 27 T8.f01 (steady flow) ---

Flow Title=Multiple
Number of Profiles=7
Profile Names=10-year,25-year,50-year,1pct_min,100-year,1pct_plu,500-year
River Rch & RM= Sweetwater Creek,Reach-1,28802
     278     400     504     316     631    1259    1004
River Rch & RM= Sweetwater Creek,Reach-1,21571
     385     561     714     452     901    1798    1455
River Rch & RM= Sweetwater Creek,Reach-1,20645
     557     827    1065     681    1359    2712    2244
River Rch & RM= Sweetwater Creek,Reach-1,16674
     550     814    1045     666    1330    2653    2182
River Rch & RM= Sweetwater Creek,Reach-1,12310
     741    1110    1437     923    1842    3674    3067
River Rch & RM= Sweetwater Creek,Reach-1,8857
     864    1302    1693    1091    2177    4344    3652
River Rch & RM= Sweetwater Creek,Reach-1,7863
    1054    1594    2078    1341    2675    5338    4500
Boundary for River Rch & Prof#=Sweetwater Creek,Reach-1,1
Up Type=0
Dn Type=3
Dn Slope=0.005
Boundary for River Rch & Prof#=Sweetwater Creek,Reach-1,2
Up Type=0
Dn Type=3
Dn Slope=0.005
Boundary for River Rch & Prof#=Sweetwater Creek,Reach-1,3
Up Type=0
Dn Type=3
Dn Slope=0.005
Boundary for River Rch & Prof#=Sweetwater Creek,Reach-1,4
Up Type=0
Dn Type=3
Dn Slope=0.005
Boundary for River Rch & Prof#=Sweetwater Creek,Reach-1,5
Up Type=0
Dn Type=3
Dn Slope=0.005
Boundary for River Rch & Prof#=Sweetwater Creek,Reach-1,6
Up Type=0
Dn Type=3
Dn Slope=0.005
Boundary for River Rch & Prof#=Sweetwater Creek,Reach-1,7
Up Type=0
Dn Type=3
Dn Slope=0.005

--- Sweetwater Creek Trib 27 T8.g01 (geometry) ---

Geom Title=Existing Conditions

River Reach=Sweetwater Creek,Reach-1
Reach XY= 30
      1366305.00      6857288.00      1365915.03      6858298.07
      1367214.79      6858848.52      1368338.58      6859721.20
      1368537.87      6860271.54      1369782.16      6861164.42
      1370363.12      6862794.08      1371249.56      6862993.25
      1371106.91      6863532.28      1371598.95      6864079.84
      1372207.47      6864193.45      1372905.00      6864880.44
      1374161.21      6864430.19      1374506.28      6863841.52
      1375244.57      6863789.04      1375506.46      6864184.47
      1376196.81      6864141.67      1377260.67      6865186.02
      1379020.39      6865587.91      1379473.38      6865337.69
      1380553.50      6865491.62      1380902.82      6866043.45
      1380908.16      6866680.35      1381102.08      6866695.91
      1381560.62      6867632.38      1382246.86      6868031.94
      1382374.47      6868708.54      1382964.80      6868798.47
      1383813.35      6869785.00      1384455.00      6869688.00

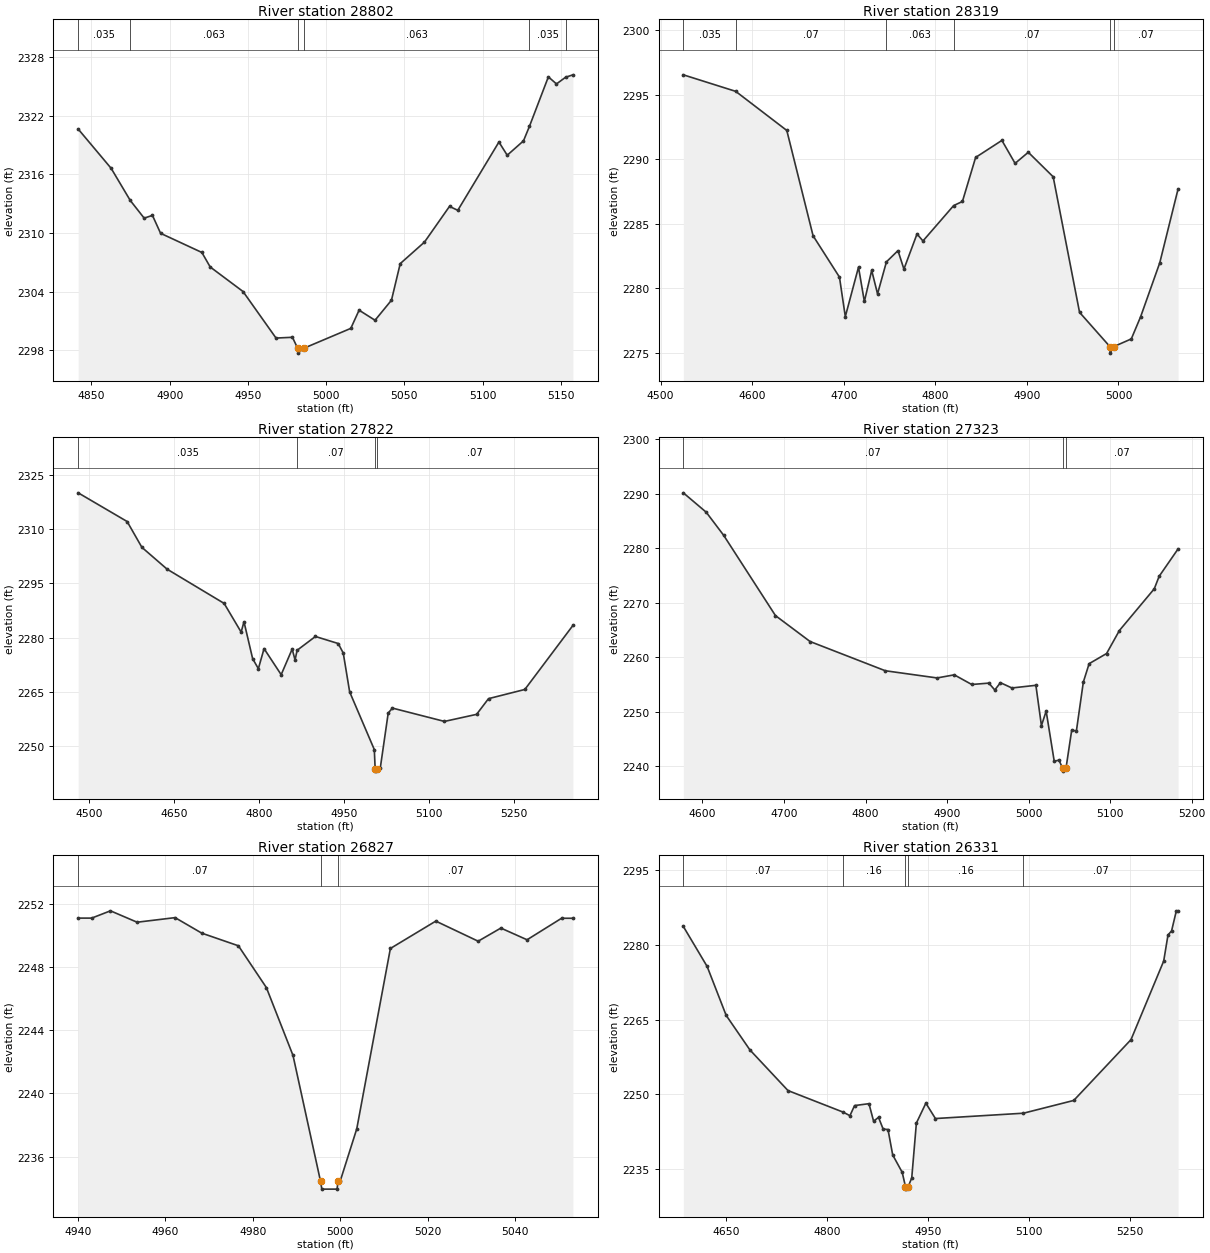
Type RM Length L Ch R = 1,28802,483,483,483
BEGIN DESCRIPTION:
Sweetwater Creek Trib 27 T8 57.0
END DESCRIPTION:
XS GIS Cut Line= 3
      1366054.97      6857437.99      1366205.33      6857488.14
      1366354.96      6857438.01
#Sta/Elev= 30
  4841.5 2320.62  4862.6 2316.60  4874.8 2313.32  4883.7 2311.51  4889.0 2311.79
  4894.2 2309.96  4920.6 2308.00  4925.9 2306.52  4946.9 2304.01  4968.0 2299.25
  4978.5 2299.33  4981.8 2298.21  4982.1 2297.71  4985.8 2298.21  5015.8 2300.24
  5021.1 2302.10  5031.3 2301.07  5041.8 2303.12  5047.4 2306.86  5062.9 2309.06
  5078.9 2312.71  5084.2 2312.31  5110.5 2319.29  5115.8 2317.94  5126.2 2319.41
  5130.0 2320.89  5142.1 2325.95  5147.3 2325.23  5153.1 2325.91  5157.8 2326.16
#Mann=6,-1,0
  4841.5   0.035       0  4874.8   0.063       0  4981.8   0.063       0
  4985.8   0.063       0  5130.0   0.035       0  5153.1   0.063       0
Bank Sta=4981.8,4985.8
Exp/Cntr=0.3,0.1

Type RM Length L Ch R = 1,28319,497,497,497
BEGIN DESCRIPTION:
Sweetwater Creek Trib 27 T8 56.0
END DESCRIPTION:
XS GIS Cut Line= 3
      1365772.11      6857651.96      1366141.28      6857951.17
      1366205.03      6857937.99
#Sta/Elev= 30
  4524.8 2296.55  4582.0 2295.27  4637.8 2292.24  4666.5 2284.08  4695.3 2280.88
  4701.7 2277.82  4716.1 2281.65  4722.5 2278.99  4730.5 2281.40  4736.9 2279.58
  4746.6 2282.06  4759.2 2282.93  4765.7 2281.50  4780.0 2284.22  4786.5 2283.68
  4820.0 2286.42  4829.6 2286.74  4844.0 2290.15  4872.7 2291.47  4887.1 2289.69
  4901.5 2290.55  4928.7 2288.65  4957.5 2278.15  4990.7 2275.49  4990.9 2274.99
  4994.7 2275.49  5014.0 2276.09  5024.2 2277.81  5045.1 2281.99  5065.1 2287.71
#Mann=6,-1,0
  4524.8   0.035       0  4582.0    0.07       0  4746.6   0.063       0
  4820.0    0.07       0  4990.7    0.07       0  4994.7    0.07       0
Bank Sta=4990.7,4994.7
Exp/Cntr=0.3,0.1

Type RM Length L Ch R = 1,27822,499,499,499
BEGIN DESCRIPTION:
Sweetwater Creek Trib 27 T8 55.0
END DESCRIPTION:
XS GIS Cut Line= 3
      1365429.12      6858385.63      1365944.78      6858327.70
      1366205.01      6858088.00
#Sta/Elev= 30
  4481.1 2320.00  4567.5 2312.08  4593.5 2304.96  4638.0 2298.93  4738.6 2289.48
  4768.6 2281.56  4773.6 2284.41  4788.9 2274.21  4799.0 2271.47  4809.0 2277.00
  4839.2 2269.81  4858.6 2276.87  4863.7 2273.86  4867.3 2276.54  4899.6 2280.35
  4939.8 2278.41  4948.7 2275.78  4960.0 2265.06  5003.5 2249.13  5005.0 2243.69
  5005.3 2243.19  5009.0 2243.69  5013.9 2243.92  5028.0 2259.21  5035.4 2260.59
  5127.2 2256.91  5183.9 2258.86  5204.9 2263.19  5269.0 2265.73  5353.8 2283.40
#Mann=4,-1,0
  4481.1   0.035       0  4867.3    0.07       0  5005.0    0.07       0
  5009.0    0.07       0
Bank Sta=5005,5009
Exp/Cntr=0.3,0.1

Type RM Length L Ch R = 1,27323,496,496,496
BEGIN DESCRIPTION:
Sweetwater Creek Trib 27 T8 54.0
END DESCRIPTION:
XS GIS Cut Line= 3
      1366105.01      6858637.99      1366411.48      6858345.69
      1366504.98      6858188.04
#Sta/Elev= 30
  4576.5 2290.20  4604.6 2286.64  4626.0 2282.40  4689.5 2267.67  4732.0 2262.91
  4824.2 2257.55  4887.7 2256.23  4908.8 2256.80  4930.2 2255.03  4951.2 2255.28
  4958.5 2254.02  4965.4 2255.36  4979.5 2254.39  5008.9 2254.88  5015.7 2247.48
  5021.5 2250.14  5031.4 2240.94  5037.2 2241.15  5041.8 2239.63  5042.1 2239.13
  5045.8 2239.63  5052.8 2246.62  5058.6 2246.52  5067.1 2255.48  5074.2 2258.85
  5095.6 2260.71  5111.3 2264.93  5154.1 2272.59  5160.1 2274.89  5183.3 2279.91
#Mann=3,-1,0
  4576.5    0.07       0  5041.8    0.07       0  5045.8    0.07       0
Bank Sta=5041.8,5045.8
Exp/Cntr=0.3,0.1

Type RM Length L Ch R = 1,26827,496,496,496
BEGIN DESCRIPTION:
Sweetwater Creek Trib 27 T8 53.0
END DESCRIPTION:
XS GIS Cut Line= 3
      1366754.99      6858638.02      1366789.59      6858589.00
      1366805.01      6858537.97
#Sta/Elev= 22
  4940.0 2251.08  4943.1 2251.08  4947.4 2251.54  4953.5 2250.82  4962.2 2251.11
  4968.3 2250.13  4976.7 2249.33  4983.1 2246.69  4989.2 2242.40  4995.5 2234.45
  4995.8 2233.95  4999.3 2233.95  4999.5 2234.45  5000.0 2234.45  5003.8 2237.76
  5011.5 2249.16  5021.9 2250.89  5031.6 2249.62  5036.8 2250.45  5042.8 2249.71
  5050.7 2251.07  5053.3 2251.07
#Mann=3,-1,0
  4940.0    0.07       0  4995.5    0.07       0  4999.5    0.07       0
Bank Sta=4995.5,4999.5
Exp/Cntr=0.3,0.1

Type RM Length L Ch R = 1,26331,495,495,495
BEGIN DESCRIPTION:
Sweetwater Creek Trib 27 T8 52.0
END DESCRIPTION:
XS GIS Cut Line= 3
      1366904.97      6859138.03      1367191.09      6858838.67
      1367304.99      6858538.03
#Sta/Elev= 30
  4585.9 2283.69  4621.3 2275.67  4649.6 2265.86  4684.9 2258.94  4741.5 2250.79
  4823.6 2246.46  4833.6 2245.75  4840.5 2247.78  4861.9 2248.16  4868.8 2244.64
  4876.1 2245.42  4883.0 2243.06  4890.2 2242.98  4897.2 2237.88  4911.3 2234.41
  4916.2 2231.53  4916.5 2231.03  4920.2 2231.53  4925.5 2233.27  4932.4 2244.27
  4946.5 2248.26  4960.7 2245.18  5091.6 2246.25  5166.4 2248.81  5251.5 2261.00
  5300.1 2276.75  5306.5 2281.98  5311.8 2282.79  5318.9 2286.82  5321.5 2286.82
#Mann=5,-1,0
  4585.9    0.07       0  4823.6    0.16       0  4916.2    0.07       0
  4920.2    0.16       0  5091.6    0.07       0
Bank Sta=4916.2,4920.2
Exp/Cntr=0.3,0.1

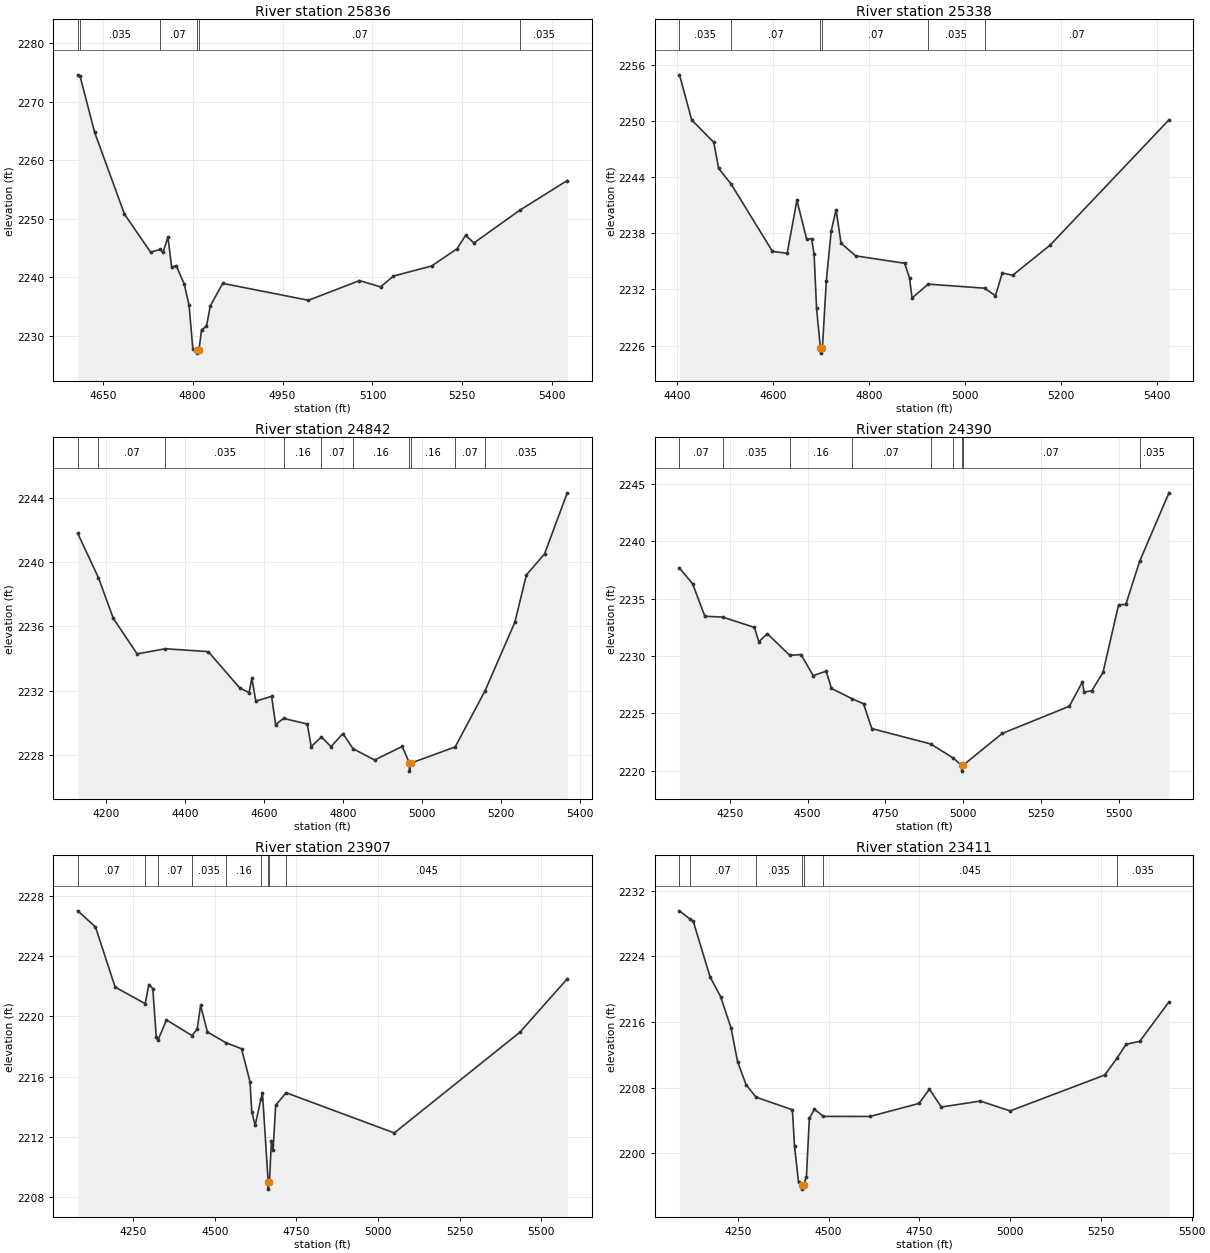
Type RM Length L Ch R = 1,25836,498,498,498
BEGIN DESCRIPTION:
Sweetwater Creek Trib 27 T8 51.0
END DESCRIPTION:
XS GIS Cut Line= 3
      1367254.99      6859388.01      1367564.97      6859148.71
      1367854.98      6858838.03
#Sta/Elev= 30
  4608.4 2274.61  4612.2 2274.39  4636.5 2264.78  4686.3 2250.79  4729.8 2244.28
  4745.3 2244.74  4750.6 2244.25  4758.8 2246.85  4765.1 2241.69  4772.6 2241.98
  4785.9 2238.86  4794.1 2235.21  4800.4 2227.66  4806.6 2227.51  4806.8 2227.01
  4810.6 2227.51  4814.9 2231.03  4823.1 2231.57  4829.4 2235.06  4850.2 2238.94
  4993.3 2236.05  5078.4 2239.42  5113.6 2238.34  5135.1 2240.19  5198.6 2241.91
  5241.1 2244.85  5255.3 2247.14  5269.4 2245.86  5346.2 2251.48  5425.0 2256.53
#Mann=6,-1,0
  4608.4    0.07       0  4612.2   0.035       0  4745.3    0.07       0
  4806.6    0.07       0  4810.6    0.07       0  5346.2   0.035       0
Bank Sta=4806.6,4810.6
Exp/Cntr=0.3,0.1

Type RM Length L Ch R = 1,25338,496,496,496
BEGIN DESCRIPTION:
Sweetwater Creek Trib 27 T8 50.0
END DESCRIPTION:
XS GIS Cut Line= 3
      1367355.03      6859537.99      1367938.30      6859421.42
      1368255.00      6859138.00
#Sta/Elev= 30
  4405.2 2254.93  4430.7 2250.11  4476.6 2247.72  4486.8 2244.94  4512.8 2243.26
  4598.9 2236.07  4629.5 2235.86  4649.9 2241.52  4670.3 2237.35  4680.5 2237.43
  4685.7 2235.75  4690.8 2229.97  4698.9 2225.70  4699.2 2225.20  4702.9 2225.70
  4711.1 2232.91  4721.3 2238.25  4731.5 2240.51  4741.8 2236.94  4772.3 2235.59
  4874.3 2234.80  4884.5 2233.23  4889.7 2231.09  4923.5 2232.57  5040.8 2232.14
  5063.5 2231.33  5077.7 2233.76  5099.4 2233.52  5177.2 2236.73  5425.0 2250.12
#Mann=6,-1,0
  4405.2   0.035       0  4512.8    0.07       0  4698.9   0.035       0
  4702.9    0.07       0  4923.5   0.035       0  5040.8    0.07       0
Bank Sta=4698.9,4702.9
Exp/Cntr=0.3,0.1

Type RM Length L Ch R = 1,24842,452,452,452
BEGIN DESCRIPTION:
Sweetwater Creek Trib 27 T8 49.0
END DESCRIPTION:
XS GIS Cut Line= 3
      1367455.05      6859738.00      1368325.52      6859707.72
      1368505.02      6859387.96
#Sta/Elev= 30
  4129.0 2241.77  4181.2 2239.03  4219.0 2236.50  4279.0 2234.30  4350.4 2234.62
  4459.1 2234.44  4539.2 2232.17  4562.3 2231.90  4569.2 2232.80  4579.2 2231.37
  4619.2 2231.67  4629.3 2229.92  4649.6 2230.30  4709.3 2229.95  4719.3 2228.55
  4745.1 2229.15  4769.3 2228.55  4799.4 2229.36  4825.1 2228.42  4879.4 2227.72
  4949.4 2228.56  4967.5 2227.53  4967.7 2227.03  4971.5 2227.53  5083.3 2228.53
  5159.0 2232.02  5234.3 2236.27  5263.4 2239.20  5309.3 2240.50  5366.7 2244.29
#Mann=10,-1,0
  4129.0   0.035       0  4181.2    0.07       0  4350.4   0.035       0
  4649.6    0.16       0  4745.1    0.07       0  4825.1    0.16       0
  4967.5    0.07       0  4971.5    0.16       0  5083.3    0.07       0
  5159.0   0.035       0
Bank Sta=4967.5,4971.5
Exp/Cntr=0.3,0.1

Type RM Length L Ch R = 1,24390,483,483,483
BEGIN DESCRIPTION:
Sweetwater Creek Trib 27 T8 48.0
END DESCRIPTION:
XS GIS Cut Line= 3
      1367604.97      6859837.99      1368475.41      6860107.83
      1368705.00      6859487.99
#Sta/Elev= 30
  4088.7 2237.67  4130.6 2236.32  4170.2 2233.47  4227.2 2233.40  4329.5 2232.50
  4343.6 2231.25  4371.0 2231.95  4443.1 2230.06  4479.2 2230.13  4518.0 2228.30
  4559.9 2228.68  4577.0 2227.17  4642.0 2226.29  4680.0 2225.84  4706.4 2223.67
  4895.8 2222.33  4967.7 2221.11  4995.2 2220.46  4995.4 2219.96  4999.2 2220.46
  5125.4 2223.25  5341.1 2225.62  5382.9 2227.74  5388.3 2226.85  5413.3 2226.98
  5449.1 2228.57  5499.2 2234.47  5522.4 2234.50  5566.6 2238.25  5661.0 2244.24
#Mann=9,-1,0
  4088.7    0.07       0  4227.2   0.035       0  4443.1    0.16       0
  4642.0    0.07       0  4895.8   0.035       0  4967.7    0.07       0
  4995.2    0.07       0  4999.2    0.07       0  5566.6   0.035       0
Bank Sta=4995.2,4999.2
Exp/Cntr=0.3,0.1

Type RM Length L Ch R = 1,23907,496,496,496
BEGIN DESCRIPTION:
Sweetwater Creek Trib 27 T8 47.0
END DESCRIPTION:
XS GIS Cut Line= 3
      1367905.00      6860688.00      1368785.07      6860417.83
      1368805.00      6859837.97
#Sta/Elev= 30
  4079.4 2227.01  4133.7 2225.94  4193.9 2221.95  4286.1 2220.85  4297.4 2222.12
  4309.5 2221.85  4320.0 2218.64  4325.3 2218.42  4351.4 2219.77  4429.8 2218.73
  4445.5 2219.17  4456.0 2220.73  4476.9 2218.97  4534.3 2218.25  4581.5 2217.86
  4607.6 2215.66  4612.9 2213.67  4623.3 2212.77  4640.9 2214.51  4645.6 2214.94
  4663.2 2209.04  4663.4 2208.54  4667.2 2209.04  4673.1 2211.72  4678.3 2211.11
  4686.1 2214.10  4717.9 2214.94  5049.9 2212.27  5434.9 2218.95  5580.2 2222.50
#Mann=9,-1,0
  4079.4    0.07       0  4286.1   0.035       0  4325.3    0.07       0
  4429.8   0.035       0  4534.3    0.16       0  4640.9    0.07       0
  4663.2   0.045       0  4667.2    0.07       0  4717.9   0.045       0
Bank Sta=4663.2,4667.2
Exp/Cntr=0.3,0.1

Type RM Length L Ch R = 1,23411,387,387,387
BEGIN DESCRIPTION:
Sweetwater Creek Trib 27 T8 46.0
END DESCRIPTION:
XS GIS Cut Line= 3
      1368805.00      6861538.00      1369171.65      6860704.70
      1369305.00      6860288.01
#Sta/Elev= 30
  4089.6 2229.56  4117.3 2228.60  4127.3 2228.31  4174.0 2221.49  4202.8 2219.12
  4231.6 2215.28  4249.5 2211.20  4272.8 2208.40  4300.4 2206.86  4400.5 2205.33
  4406.4 2200.87  4417.4 2196.55  4427.3 2196.16  4427.5 2195.66  4431.3 2196.16
  4439.2 2197.19  4447.2 2204.28  4461.1 2205.39  4485.9 2204.52  4614.0 2204.51
  4749.1 2206.10  4777.9 2207.84  4810.7 2205.66  4917.9 2206.39  5000.0 2205.19
  5260.7 2209.56  5293.9 2211.58  5319.7 2213.31  5357.1 2213.66  5437.5 2218.47
#Mann=7,-1,0
  4089.6   0.035       0  4117.3    0.07       0  4300.4   0.035       0
  4427.3   0.045       0  4431.3   0.035       0  4485.9   0.045       0
  5293.9   0.035       0
Bank Sta=4427.3,4431.3
Exp/Cntr=0.3,0.1

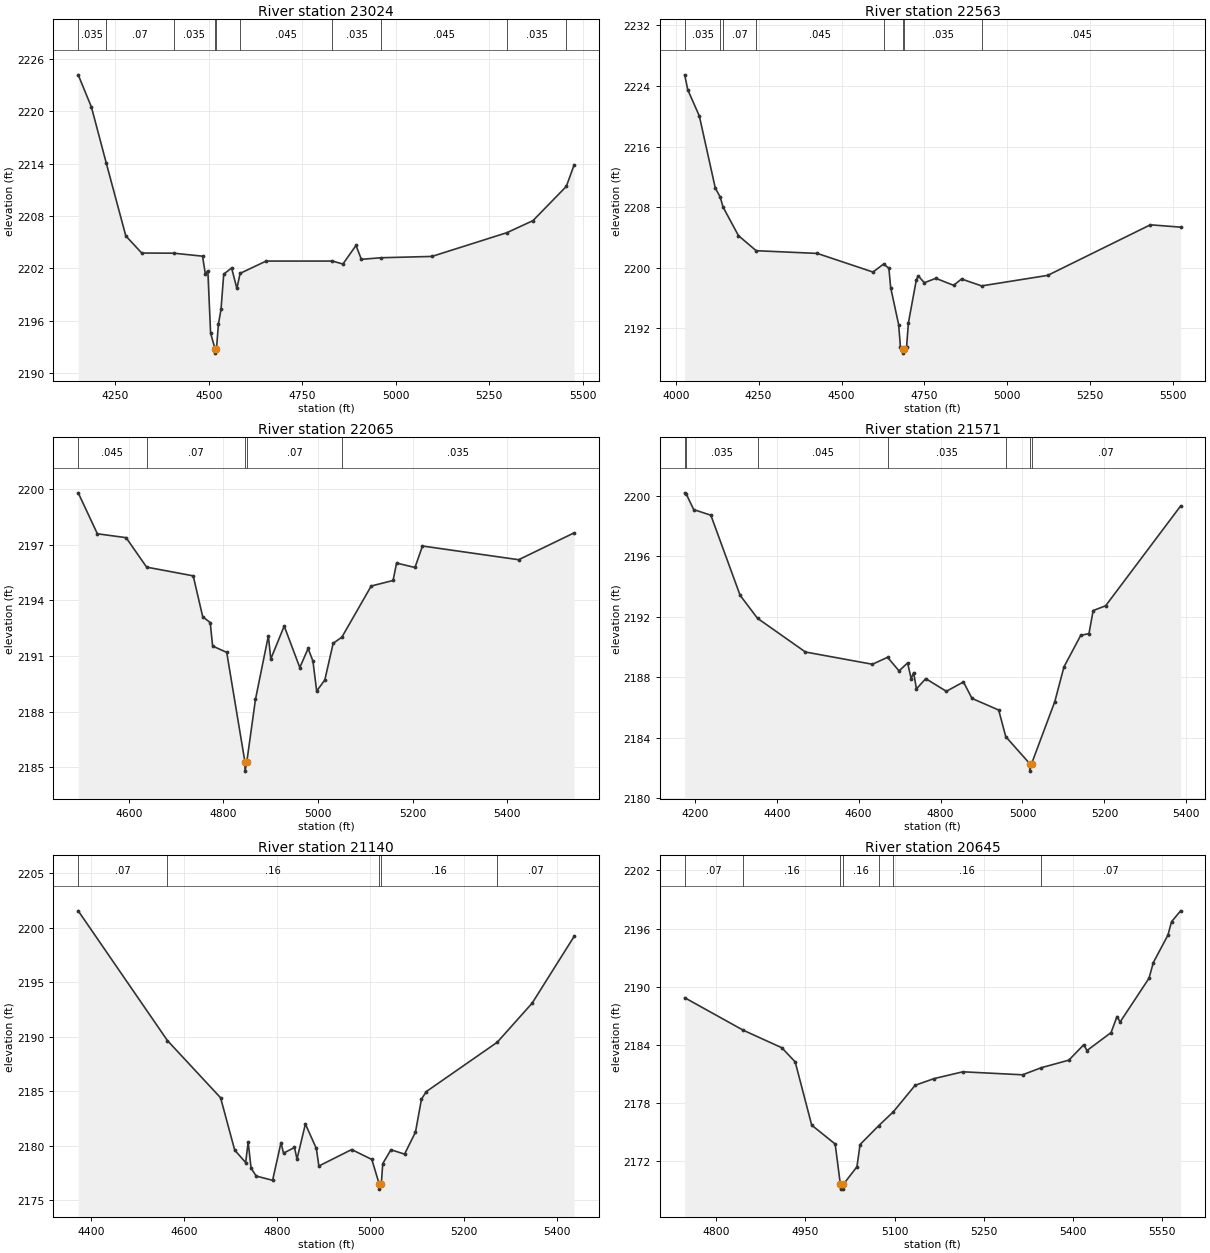
Type RM Length L Ch R = 1,23024,461,461,461
BEGIN DESCRIPTION:
Sweetwater Creek Trib 27 T8 45.0
END DESCRIPTION:
XS GIS Cut Line= 3
      1368905.01      6861537.99      1369481.69      6860914.62
      1369505.00      6860437.99
#Sta/Elev= 30
  4150.8 2224.16  4186.2 2220.46  4226.0 2214.03  4278.1 2205.72  4320.6 2203.76
  4406.5 2203.74  4483.3 2203.40  4490.7 2201.41  4497.5 2201.71  4504.9 2194.60
  4516.6 2192.80  4516.8 2192.30  4520.6 2192.80  4525.8 2195.62  4532.7 2197.31
  4540.0 2201.34  4561.0 2202.05  4575.2 2199.71  4583.8 2201.43  4653.4 2202.84
  4830.7 2202.84  4858.7 2202.50  4893.8 2204.63  4908.0 2203.04  4961.4 2203.22
  5096.7 2203.37  5297.4 2206.09  5367.1 2207.47  5456.3 2211.39  5477.2 2213.86
#Mann=10,-1,0
  4150.8   0.035       0  4226.0    0.07       0  4406.5   0.035       0
  4516.6   0.045       0  4520.6   0.035       0  4583.8   0.045       0
  4830.7   0.035       0  4961.4   0.045       0  5297.4   0.035       0
  5456.3   0.045       0
Bank Sta=4516.6,4520.6
Exp/Cntr=0.3,0.1

Type RM Length L Ch R = 1,22563,498,498,498
BEGIN DESCRIPTION:
Sweetwater Creek Trib 27 T8 44.0
END DESCRIPTION:
XS GIS Cut Line= 3
      1368904.96      6861588.01      1369805.43      6861219.64
      1369908.91      6860707.80
#Sta/Elev= 30
  4027.1 2225.48  4036.4 2223.51  4071.3 2220.04  4119.3 2210.54  4134.4 2209.32
  4142.6 2208.03  4189.2 2204.24  4242.6 2202.25  4426.9 2201.89  4594.7 2199.43
  4626.9 2200.49  4642.7 2199.93  4648.1 2197.38  4672.1 2192.50  4677.5 2189.55
  4684.2 2189.22  4684.5 2188.72  4688.2 2189.22  4696.1 2189.53  4701.5 2192.70
  4725.5 2198.41  4730.9 2198.94  4749.5 2198.02  4784.3 2198.60  4837.8 2197.68
  4861.8 2198.51  4922.2 2197.60  5121.5 2198.99  5431.0 2205.67  5522.2 2205.36
#Mann=8,-1,0
  4027.1   0.035       0  4134.4   0.045       0  4142.6    0.07       0
  4242.6   0.045       0  4626.9   0.035       0  4684.2   0.045       0
  4688.2   0.035       0  4922.2   0.045       0
Bank Sta=4684.2,4688.2
Exp/Cntr=0.3,0.1

Type RM Length L Ch R = 1,22065,494,494,494
BEGIN DESCRIPTION:
Sweetwater Creek Trib 27 T8 43.0
END DESCRIPTION:
XS GIS Cut Line= 3
      1369455.00      6861588.00      1369955.60      6861669.57
      1370177.99      6861175.52
#Sta/Elev= 30
  4492.8 2199.81  4533.3 2197.60  4594.1 2197.39  4637.5 2195.80  4736.0 2195.33
  4756.2 2193.12  4772.0 2192.81  4777.1 2191.54  4806.9 2191.20  4845.4 2185.29
  4845.7 2184.79  4849.4 2185.29  4867.7 2188.66  4895.0 2192.09  4900.1 2190.84
  4928.5 2192.62  4961.5 2190.38  4979.1 2191.41  4989.3 2190.73  4997.2 2189.11
  5014.4 2189.71  5032.1 2191.69  5050.5 2192.02  5112.5 2194.78  5158.8 2195.08
  5166.2 2196.02  5205.1 2195.78  5221.0 2196.94  5424.4 2196.20  5541.8 2197.65
#Mann=5,-1,0
  4492.8   0.045       0  4637.5    0.07       0  4845.4    0.07       0
  4849.4    0.07       0  5050.5   0.035       0
Bank Sta=4845.4,4849.4
Exp/Cntr=0.3,0.1

Type RM Length L Ch R = 1,21571,431,431,431
BEGIN DESCRIPTION:
Sweetwater Creek Trib 27 T8 42.0
END DESCRIPTION:
XS GIS Cut Line= 3
      1369505.00      6862538.00      1370175.39      6862057.84
      1370555.01      6861988.00
#Sta/Elev= 30
  4175.4 2200.19  4179.2 2200.11  4197.5 2199.08  4239.3 2198.71  4310.7 2193.41
  4353.2 2191.89  4470.2 2189.66  4633.6 2188.85  4670.7 2189.31  4698.7 2188.41
  4719.6 2188.94  4728.2 2187.90  4734.3 2188.29  4741.2 2187.22  4763.8 2187.90
  4814.1 2187.06  4855.9 2187.68  4876.8 2186.59  4941.9 2185.82  4959.2 2184.06
  5017.5 2182.28  5017.9 2181.78  5022.3 2182.28  5078.9 2186.38  5101.3 2188.68
  5142.2 2190.76  5162.3 2190.88  5172.5 2192.40  5203.0 2192.72  5386.0 2199.32
#Mann=7,-1,0
  4175.4    0.07       0  4179.2   0.035       0  4353.2   0.045       0
  4670.7   0.035       0  4959.2    0.07       0  5017.5    0.07       0
  5022.3    0.07       0
Bank Sta=5017.5,5022.3
Exp/Cntr=0.3,0.1

Type RM Length L Ch R = 1,21140,495,495,495
BEGIN DESCRIPTION:
Sweetwater Creek Trib 27 T8 41.0
END DESCRIPTION:
XS GIS Cut Line= 3
      1370005.01      6863037.97      1370254.79      6862463.09
      1370654.97      6862288.01
#Sta/Elev= 30
  4373.2 2201.56  4564.6 2189.66  4678.5 2184.42  4708.8 2179.62  4732.3 2178.48
  4737.7 2180.36  4743.9 2177.97  4754.8 2177.24  4790.1 2176.85  4808.1 2180.31
  4813.5 2179.34  4837.0 2179.86  4842.4 2178.80  4860.4 2182.01  4883.9 2179.77
  4889.3 2178.16  4959.7 2179.67  5002.9 2178.76  5018.5 2176.54  5018.8 2176.04
  5023.3 2176.54  5026.3 2178.38  5043.9 2179.65  5073.1 2179.25  5096.5 2181.27
  5109.4 2184.30  5119.9 2184.99  5271.9 2189.51  5346.8 2193.10  5436.8 2199.22
#Mann=5,-1,0
  4373.2    0.07       0  4564.6    0.16       0  5018.5    0.07       0
  5023.3    0.16       0  5271.9    0.07       0
Bank Sta=5018.5,5023.3
Exp/Cntr=0.3,0.1

Type RM Length L Ch R = 1,20645,497,497,497
BEGIN DESCRIPTION:
Sweetwater Creek Trib 27 T8 40.0
END DESCRIPTION:
XS GIS Cut Line= 3
      1370254.99      6863038.01      1370456.45      6862884.47
      1370654.99      6862338.02
#Sta/Elev= 30
  4746.7 2188.88  4845.2 2185.53  4910.2 2183.72  4932.7 2182.26  4960.5 2175.74
  5000.0 2173.79  5008.7 2169.64  5009.1 2169.14  5013.5 2169.14  5013.8 2169.64
  5036.6 2171.44  5041.9 2173.74  5073.0 2175.67  5097.8 2177.11  5134.6 2179.85
  5166.5 2180.54  5214.9 2181.24  5315.4 2180.93  5346.3 2181.65  5393.2 2182.44
  5418.4 2184.03  5423.8 2183.43  5464.4 2185.29  5474.3 2186.94  5479.6 2186.38
  5528.2 2190.89  5535.5 2192.51  5560.1 2195.34  5566.1 2196.72  5581.4 2197.84
#Mann=7,-1,0
  4746.7    0.07       0  4845.2    0.16       0  5008.7    0.07       0
  5013.8    0.16       0  5073.0    0.07       0  5097.8    0.16       0
  5346.3    0.07       0
Bank Sta=5008.7,5013.8
Exp/Cntr=0.3,0.1

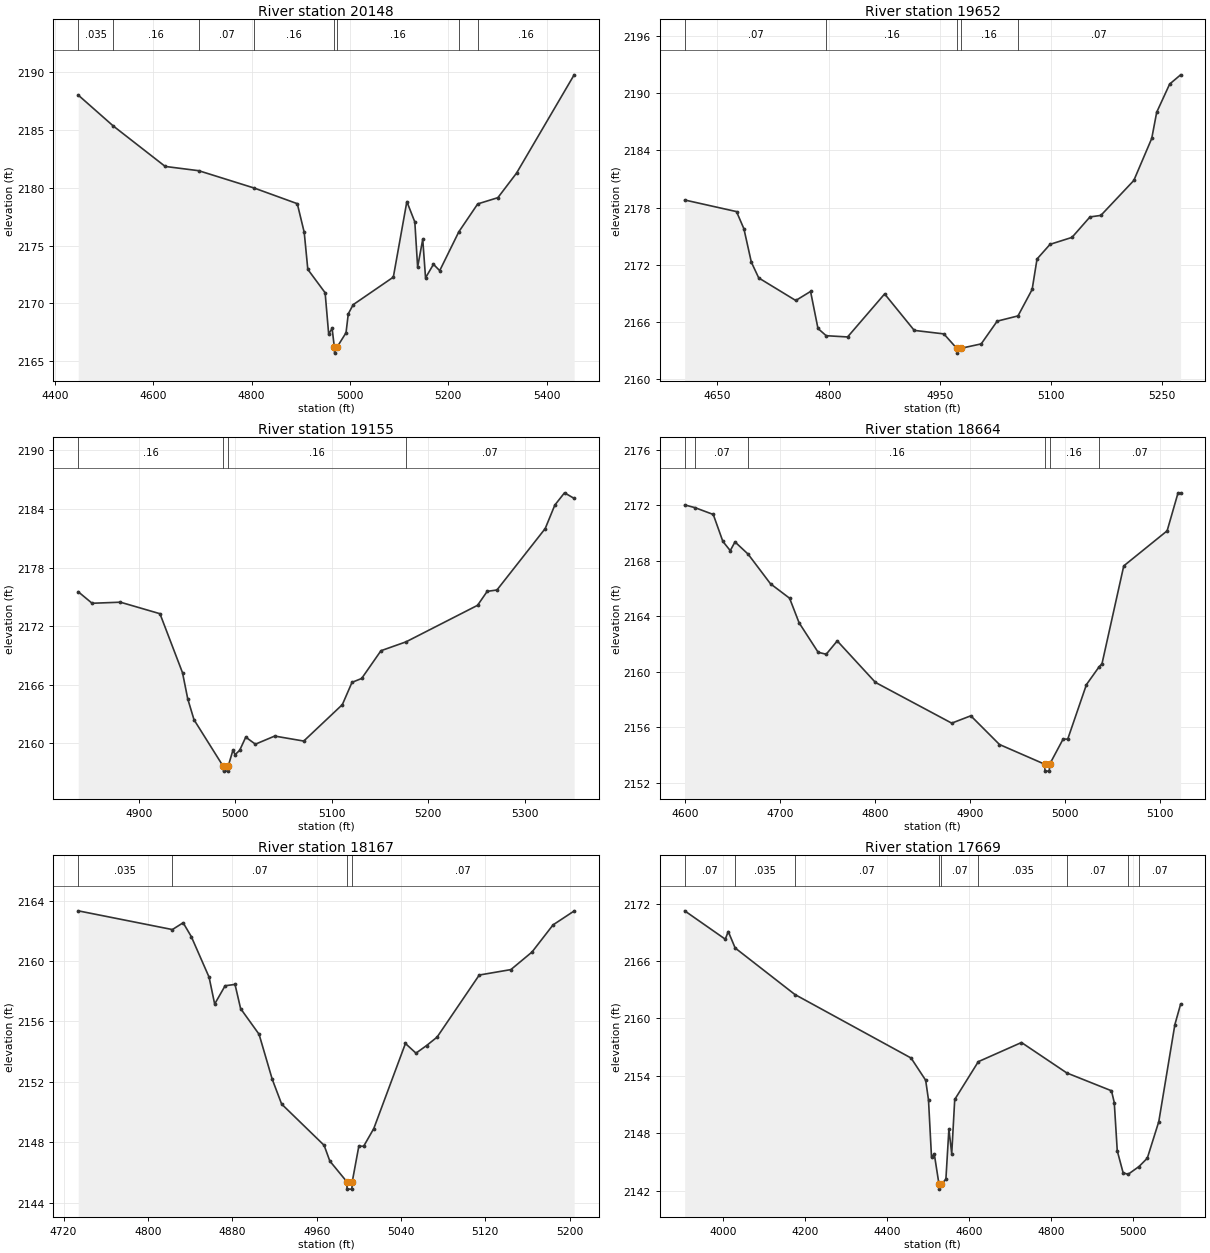
Type RM Length L Ch R = 1,20148,496,496,496
BEGIN DESCRIPTION:
Sweetwater Creek Trib 27 T8 39.0
END DESCRIPTION:
XS GIS Cut Line= 3
      1370555.02      6863237.98      1370936.41      6862838.23
      1371154.98      6862438.03
#Sta/Elev= 30
  4447.5 2188.01  4519.0 2185.33  4624.4 2181.84  4692.7 2181.47  4805.5 2179.97
  4893.0 2178.62  4907.1 2176.14  4914.4 2172.94  4949.6 2170.92  4956.8 2167.35
  4963.8 2167.84  4968.4 2166.20  4968.8 2165.70  4973.6 2166.20  4992.1 2167.46
  4996.7 2169.10  5006.7 2169.89  5088.3 2172.27  5115.8 2178.80  5132.0 2177.04
  5137.7 2173.14  5148.1 2175.54  5153.8 2172.21  5169.9 2173.38  5182.6 2172.83
  5221.5 2176.19  5259.9 2178.60  5300.9 2179.14  5338.8 2181.26  5456.0 2189.76
#Mann=8,-1,0
  4447.5   0.035       0  4519.0    0.16       0  4692.7    0.07       0
  4805.5    0.16       0  4968.4    0.07       0  4973.6    0.16       0
  5221.5    0.07       0  5259.9    0.16       0
Bank Sta=4968.4,4973.6
Exp/Cntr=0.3,0.1

Type RM Length L Ch R = 1,19652,497,497,497
BEGIN DESCRIPTION:
Sweetwater Creek Trib 27 T8 38.0
END DESCRIPTION:
XS GIS Cut Line= 3
      1370905.02      6863088.00      1371299.32      6863085.61
      1371554.98      6863187.99
#Sta/Elev= 30
  4605.7 2178.79  4675.7 2177.57  4685.7 2175.76  4695.7 2172.26  4705.7 2170.60
  4755.7 2168.23  4775.7 2169.18  4785.7 2165.29  4796.8 2164.53  4825.7 2164.40
  4875.7 2168.92  4915.7 2165.09  4955.7 2164.72  4973.1 2163.20  4973.5 2162.70
  4978.3 2163.20  5006.1 2163.67  5027.7 2166.06  5055.8 2166.61  5074.9 2169.39
  5081.5 2172.59  5099.1 2174.13  5128.7 2174.86  5153.0 2177.01  5167.7 2177.17
  5212.2 2180.84  5236.4 2185.26  5243.1 2188.01  5260.6 2190.97  5275.4 2191.94
#Mann=5,-1,0
  4605.7    0.07       0  4796.8    0.16       0  4973.1    0.07       0
  4978.3    0.16       0  5055.8    0.07       0
Bank Sta=4973.1,4978.3
Exp/Cntr=0.3,0.1

Type RM Length L Ch R = 1,19155,491,491,491
BEGIN DESCRIPTION:
Sweetwater Creek Trib 27 T8 37.0
END DESCRIPTION:
XS GIS Cut Line= 3
      1370954.99      6863438.00      1371104.20      6863503.13
      1371454.97      6863488.00
#Sta/Elev= 30
  4837.2 2175.52  4851.6 2174.34  4880.9 2174.45  4921.9 2173.27  4945.3 2167.22
  4950.7 2164.55  4957.2 2162.41  4987.4 2157.65  4987.8 2157.15  4992.2 2157.15
  4992.6 2157.65  4997.5 2159.28  4999.8 2158.84  5004.5 2159.28  5010.8 2160.63
  5020.8 2159.91  5040.8 2160.74  5070.9 2160.23  5110.9 2163.96  5120.9 2166.24
  5130.9 2166.64  5150.9 2169.48  5176.9 2170.39  5251.0 2174.13  5261.0 2175.56
  5271.1 2175.70  5321.1 2181.99  5331.1 2184.40  5341.1 2185.65  5351.1 2185.08
#Mann=4,-1,0
  4837.2    0.16       0  4987.4    0.07       0  4992.6    0.16       0
  5176.9    0.07       0
Bank Sta=4987.4,4992.6
Exp/Cntr=0.3,0.1

Type RM Length L Ch R = 1,18664,497,497,497
BEGIN DESCRIPTION:
Sweetwater Creek Trib 27 T8 36.0
END DESCRIPTION:
XS GIS Cut Line= 3
      1371005.03      6863888.00      1371403.49      6863848.63
      1371454.99      6863738.03
#Sta/Elev= 30
  4599.6 2172.03  4610.5 2171.83  4629.7 2171.34  4639.8 2169.40  4647.6 2168.73
  4652.6 2169.36  4666.4 2168.48  4690.0 2166.34  4710.1 2165.30  4720.1 2163.53
  4740.2 2161.40  4748.7 2161.26  4760.3 2162.22  4800.5 2159.23  4880.9 2156.29
  4901.0 2156.82  4931.2 2154.75  4978.8 2153.33  4979.2 2152.83  4983.6 2152.83
  4984.1 2153.33  4998.2 2155.14  5003.1 2155.14  5022.8 2159.07  5036.0 2160.34
  5039.2 2160.58  5062.1 2167.63  5107.8 2170.16  5119.3 2172.90  5122.0 2172.90
#Mann=6,-1,0
  4599.6    0.16       0  4610.5    0.07       0  4666.4    0.16       0
  4978.8    0.07       0  4984.1    0.16       0  5036.0    0.07       0
Bank Sta=4978.8,4984.1
Exp/Cntr=0.3,0.1

Type RM Length L Ch R = 1,18167,498,498,498
BEGIN DESCRIPTION:
Sweetwater Creek Trib 27 T8 35.0
END DESCRIPTION:
XS GIS Cut Line= 3
      1371505.03      6864237.99      1371753.28      6864142.16
      1371755.00      6863937.97
#Sta/Elev= 30
  4733.9 2163.32  4823.2 2162.08  4833.4 2162.53  4841.1 2161.62  4858.0 2158.93
  4863.3 2157.15  4873.2 2158.36  4882.6 2158.45  4887.9 2156.85  4905.4 2155.15
  4917.9 2152.17  4926.8 2150.53  4967.1 2147.80  4972.5 2146.76  4988.5 2145.40
  4988.9 2144.90  4993.4 2144.90  4993.8 2145.40  5000.0 2147.74  5004.6 2147.74
  5014.2 2148.91  5044.2 2154.54  5054.2 2153.90  5064.2 2154.40  5074.2 2154.96
  5114.2 2159.07  5144.2 2159.43  5164.2 2160.59  5184.2 2162.39  5204.2 2163.31
#Mann=4,-1,0
  4733.9   0.035       0  4823.2    0.07       0  4988.5    0.07       0
  4993.8    0.07       0
Bank Sta=4988.5,4993.8
Exp/Cntr=0.3,0.1

Type RM Length L Ch R = 1,17669,497,497,497
BEGIN DESCRIPTION:
Sweetwater Creek Trib 27 T8 34.0
END DESCRIPTION:
XS GIS Cut Line= 3
      1371455.01      6864987.99      1372203.55      6864191.53
      1372255.00      6864088.01
#Sta/Elev= 30
  3907.0 2171.24  4005.9 2168.28  4013.2 2169.08  4030.0 2167.36  4175.7 2162.50
  4458.7 2155.87  4494.3 2153.55  4501.2 2151.49  4508.5 2145.54  4515.3 2145.84
  4526.8 2142.68  4527.2 2142.18  4532.2 2142.68  4543.6 2143.22  4550.9 2148.45
  4557.8 2145.87  4565.1 2151.54  4622.6 2155.49  4727.8 2157.49  4838.3 2154.31
  4947.1 2152.45  4953.9 2151.22  4961.2 2146.18  4975.4 2143.90  4987.4 2143.72
  5014.2 2144.54  5034.4 2145.41  5062.4 2149.23  5101.6 2159.36  5115.6 2161.50
#Mann=9,-1,0
  3907.0    0.07       0  4030.0   0.035       0  4175.7    0.07       0
  4526.8    0.07       0  4532.2    0.07       0  4622.6   0.035       0
  4838.3    0.07       0  4987.4    0.16       0  5014.2    0.07       0
Bank Sta=4526.8,4532.2
Exp/Cntr=0.3,0.1

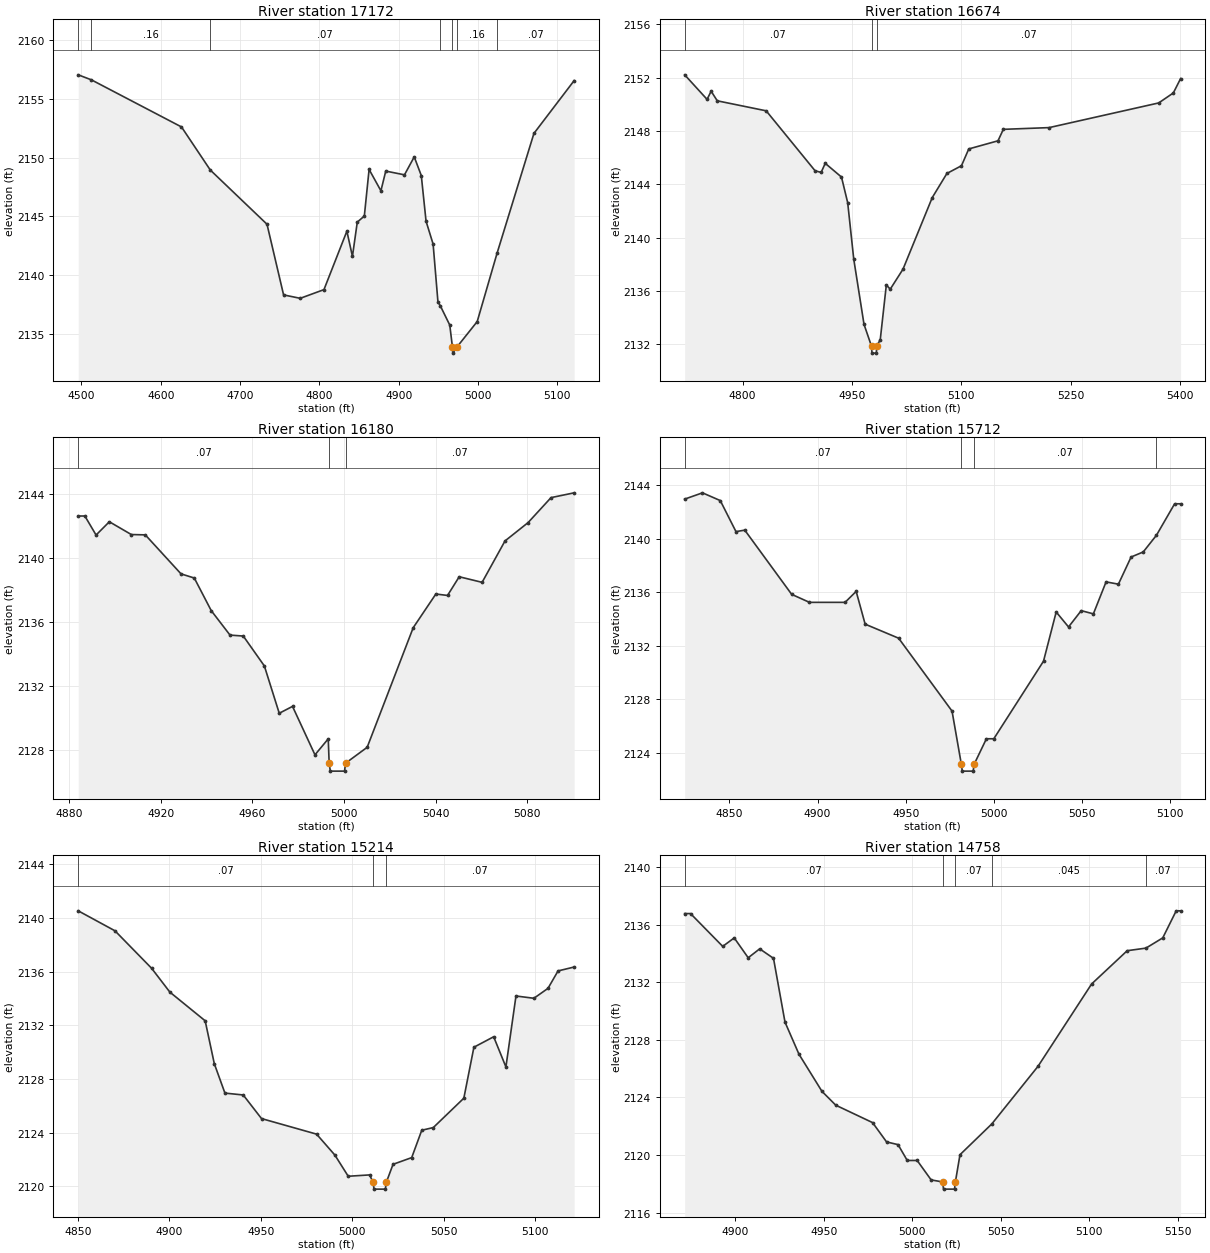
Type RM Length L Ch R = 1,17172,498,498,498
BEGIN DESCRIPTION:
Sweetwater Creek Trib 27 T8 33.0
END DESCRIPTION:
XS GIS Cut Line= 3
      1372104.97      6864788.02      1372521.75      6864504.46
      1372555.00      6864388.01
#Sta/Elev= 30
  4495.9 2157.05  4512.6 2156.62  4626.1 2152.61  4662.4 2148.94  4733.9 2144.32
  4754.8 2138.30  4775.8 2138.01  4805.7 2138.75  4834.6 2143.73  4841.6 2141.58
  4847.7 2144.50  4856.6 2145.02  4862.6 2148.99  4877.5 2147.17  4883.6 2148.85
  4907.2 2148.53  4919.5 2150.06  4928.4 2148.47  4934.4 2144.58  4943.3 2142.63
  4949.4 2137.70  4952.4 2137.37  4964.3 2135.73  4967.7 2133.84  4968.1 2133.34
  4973.1 2133.84  4998.9 2136.03  5024.0 2141.87  5070.4 2152.06  5121.1 2156.56
#Mann=7,-1,0
  4495.9    0.07       0  4512.6    0.16       0  4662.4    0.07       0
  4952.4    0.16       0  4967.7    0.07       0  4973.1    0.16       0
  5024.0    0.07       0
Bank Sta=4967.7,4973.1
Exp/Cntr=0.3,0.1

Type RM Length L Ch R = 1,16674,494,494,494
BEGIN DESCRIPTION:
Sweetwater Creek Trib 27 T8 32.0
END DESCRIPTION:
XS GIS Cut Line= 3
      1372705.01      6865087.97      1372830.03      6864838.10
      1372855.00      6864437.98
#Sta/Elev= 30
  4720.6 2152.21  4751.3 2150.37  4756.9 2150.98  4765.3 2150.26  4832.4 2149.51
  4899.5 2145.01  4907.8 2144.89  4913.4 2145.57  4935.7 2144.54  4944.2 2142.62
  4952.5 2138.39  4966.6 2133.49  4977.0 2131.83  4977.5 2131.33  4983.5 2131.33
  4984.0 2131.83  4988.9 2132.35  4997.2 2136.44  5002.6 2136.13  5020.1 2137.63
  5060.2 2143.00  5080.3 2144.81  5100.3 2145.39  5110.3 2146.65  5150.4 2147.26
  5157.7 2148.12  5220.5 2148.25  5370.8 2150.10  5390.9 2150.85  5400.9 2151.93
#Mann=3,-1,0
  4720.6    0.07       0  4977.0    0.07       0  4984.0    0.07       0
Bank Sta=4977,4984
Exp/Cntr=0.3,0.1

Type RM Length L Ch R = 1,16180,468,468,468
BEGIN DESCRIPTION:
Sweetwater Creek Trib 27 T8 31.0
END DESCRIPTION:
XS GIS Cut Line= 3
      1373355.00      6864938.00      1373295.93      6864838.05
      1373305.00      6864737.96
#Sta/Elev= 30
  4883.9 2142.61  4886.8 2142.61  4891.7 2141.42  4897.5 2142.25  4907.1 2141.45
  4913.2 2141.43  4928.8 2138.99  4934.6 2138.73  4942.0 2136.69  4950.2 2135.16
  4956.0 2135.10  4965.2 2133.23  4971.7 2130.27  4977.5 2130.70  4987.3 2127.67
  4993.1 2128.67  4993.5 2127.15  4994.0 2126.65  5000.2 2126.65  5000.7 2127.15
  5010.1 2128.14  5030.2 2135.62  5040.1 2137.73  5045.2 2137.64  5050.3 2138.81
  5060.3 2138.46  5070.3 2141.05  5080.4 2142.20  5090.4 2143.76  5100.5 2144.06
#Mann=3,-1,0
  4883.9    0.07       0  4993.5    0.07       0  5000.7    0.07       0
Bank Sta=4993.5,5000.7
Exp/Cntr=0.3,0.1

Type RM Length L Ch R = 1,15712,498,498,498
BEGIN DESCRIPTION:
Sweetwater Creek Trib 27 T8 30.0
END DESCRIPTION:
XS GIS Cut Line= 3
      1373705.00      6864787.98      1373678.31      6864614.62
      1373605.03      6864538.03
#Sta/Elev= 30
  4824.6 2142.95  4834.7 2143.42  4844.8 2142.84  4853.7 2140.52  4858.7 2140.63
  4885.3 2135.83  4895.4 2135.23  4915.6 2135.23  4921.9 2136.05  4927.0 2133.60
  4946.0 2132.55  4976.3 2127.10  4981.6 2123.11  4982.1 2122.61  4988.3 2122.61
  4988.8 2123.11  4995.8 2125.03  5000.0 2125.03  5028.2 2130.83  5035.4 2134.51
  5042.4 2133.39  5049.6 2134.61  5056.5 2134.37  5063.7 2136.76  5070.7 2136.59
  5077.9 2138.62  5084.8 2139.00  5092.3 2140.25  5102.6 2142.60  5106.0 2142.60
#Mann=4,-1,0
  4824.6    0.07       0  4981.6    0.07       0  4988.8    0.07       0
  5092.3   0.045       0
Bank Sta=4981.6,4988.8
Exp/Cntr=0.3,0.1

Type RM Length L Ch R = 1,15214,456,456,456
BEGIN DESCRIPTION:
Sweetwater Creek Trib 27 T8 29.0
END DESCRIPTION:
XS GIS Cut Line= 3
      1374105.00      6864588.00      1374115.19      6864438.45
      1374004.99      6864388.00
#Sta/Elev= 30
  4850.1 2140.54  4870.2 2139.05  4890.2 2136.26  4900.2 2134.48  4919.5 2132.34
  4924.5 2129.14  4930.3 2126.95  4940.3 2126.81  4950.3 2125.05  4980.4 2123.89
  4990.4 2122.33  4997.7 2120.75  5009.4 2120.85  5011.3 2120.29  5011.8 2119.79
  5018.0 2119.79  5018.5 2120.29  5022.2 2121.64  5032.4 2122.14  5037.9 2124.18
  5044.2 2124.38  5060.9 2126.57  5066.4 2130.37  5077.2 2131.15  5083.9 2128.90
  5089.4 2134.19  5099.2 2134.02  5106.9 2134.76  5112.4 2136.06  5121.2 2136.35
#Mann=3,-1,0
  4850.1    0.07       0  5011.3    0.07       0  5018.5    0.07       0
Bank Sta=5011.3,5018.5
Exp/Cntr=0.3,0.1

Type RM Length L Ch R = 1,14758,285,285,285
BEGIN DESCRIPTION:
Sweetwater Creek Trib 27 T8 28.0
END DESCRIPTION:
XS GIS Cut Line= 3
      1374455.01      6864188.01      1374355.60      6864106.44
      1374205.02      6864088.00
#Sta/Elev= 30
  4871.4 2136.77  4874.7 2136.77  4892.9 2134.49  4899.4 2135.08  4907.3 2133.70
  4913.8 2134.32  4921.6 2133.66  4928.1 2129.23  4936.0 2127.00  4949.0 2124.42
  4956.8 2123.46  4977.6 2122.25  4985.5 2120.91  4992.0 2120.72  4997.2 2119.62
  5002.8 2119.62  5010.7 2118.27  5017.2 2118.13  5017.7 2117.63  5023.9 2117.63
  5024.4 2118.13  5027.0 2120.02  5045.0 2122.16  5071.1 2126.16  5101.4 2131.88
  5121.5 2134.19  5132.1 2134.37  5141.6 2135.08  5149.2 2136.96  5151.7 2136.96
#Mann=5,-1,0
  4871.4    0.07       0  5017.2    0.07       0  5024.4    0.07       0
  5045.0   0.045       0  5132.1    0.07       0
Bank Sta=5017.2,5024.4
Exp/Cntr=0.3,0.1