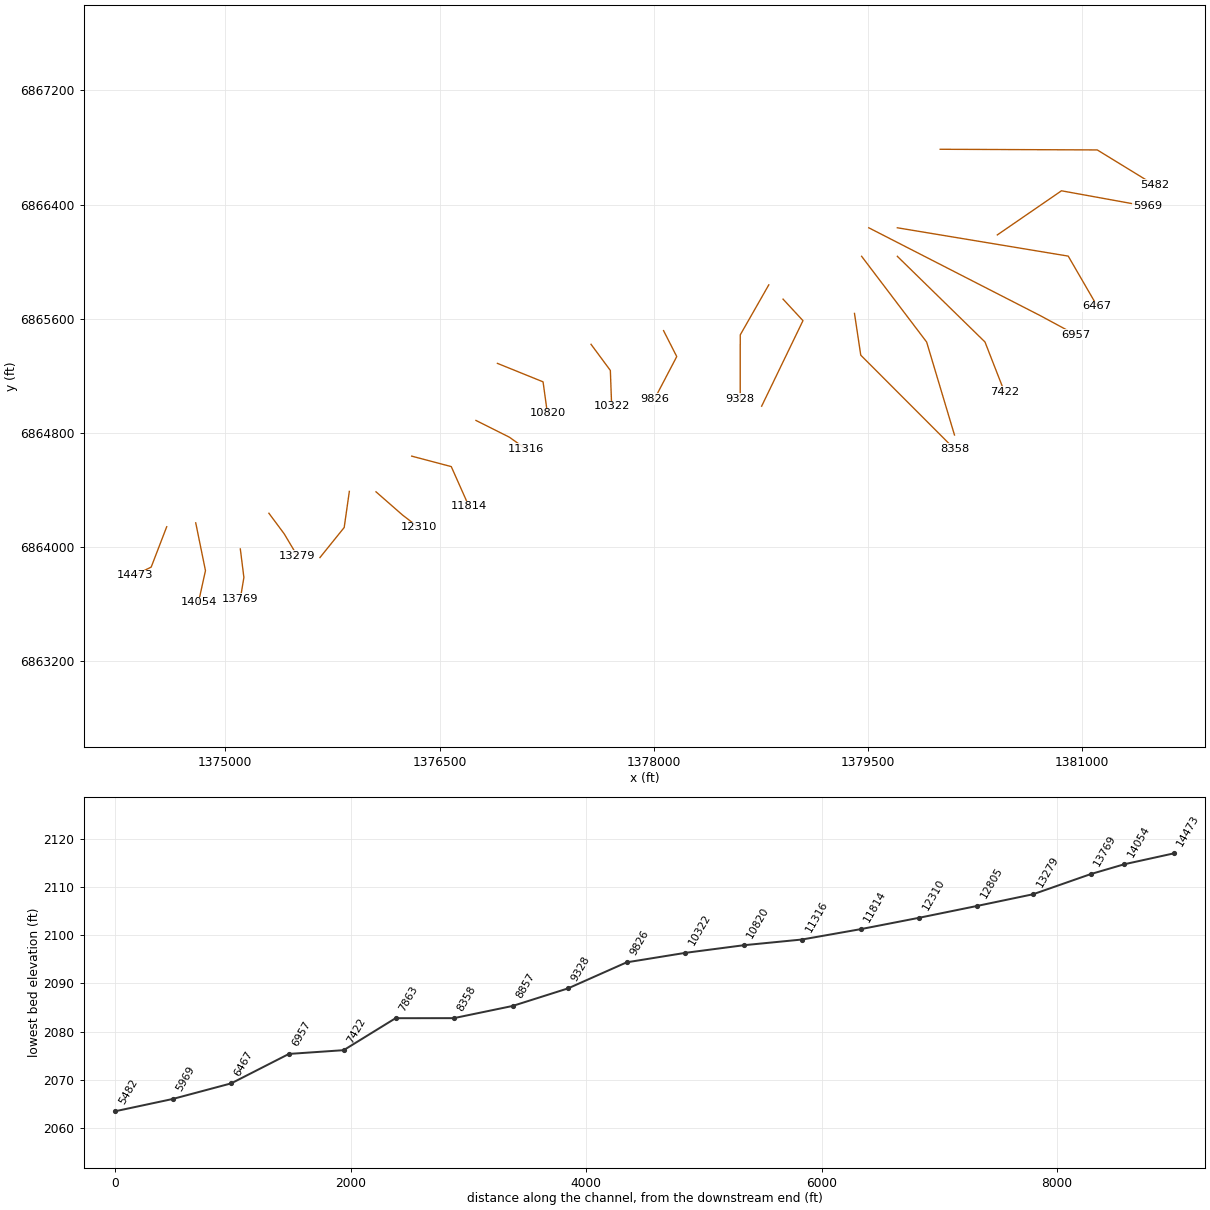
HEC-RAS study Sweetwater Creek Trib 27 T8.prj: Sweetwater Creek Trib 27 T8 Base Level Engineering

--- Sweetwater Creek Trib 27 T8.g01 (geometry) --- (continued)

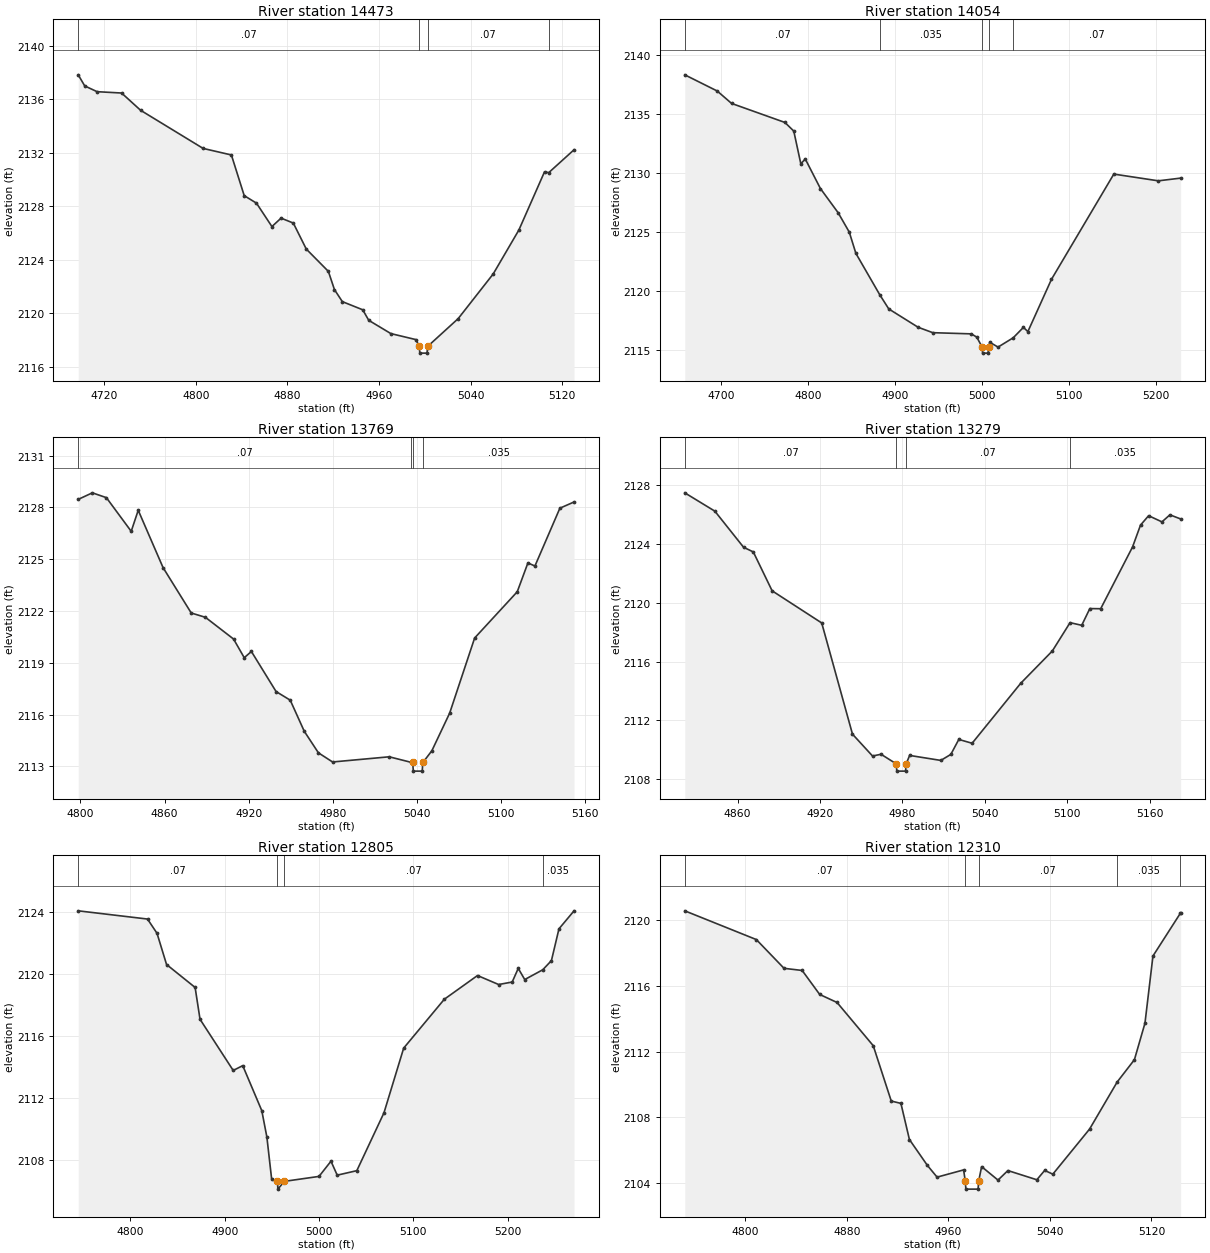
Type RM Length L Ch R = 1,14473,419,419,419
BEGIN DESCRIPTION:
Sweetwater Creek Trib 27 T8 27.1
END DESCRIPTION:
XS GIS Cut Line= 3
      1374589.75      6864143.36      1374481.10      6863860.72
      1374364.38      6863802.81
#Sta/Elev= 30
  4697.2 2137.81  4702.9 2136.98  4713.7 2136.55  4735.1 2136.45  4751.7 2135.16
  4806.3 2132.31  4831.0 2131.82  4842.2 2128.78  4852.9 2128.22  4866.4 2126.47
  4874.4 2127.10  4885.1 2126.73  4896.4 2124.79  4915.7 2123.12  4921.0 2121.76
  4927.9 2120.86  4945.7 2120.25  4951.0 2119.46  4970.3 2118.47  4992.2 2118.02
  4995.1 2117.51  4995.6 2117.01  5001.9 2117.01  5002.4 2117.51  5029.1 2119.59
  5059.7 2122.93  5082.1 2126.21  5104.5 2130.56  5108.2 2130.50  5130.3 2132.21
#Mann=4,-1,0
  4697.2    0.07       0  4995.1    0.07       0  5002.4    0.07       0
  5108.2   0.045       0
Bank Sta=4995.1,5002.4
Exp/Cntr=0.3,0.1

Type RM Length L Ch R = 1,14054,285,285,285
BEGIN DESCRIPTION:
Sweetwater Creek Trib 27 T8 27.0
END DESCRIPTION:
XS GIS Cut Line= 3
      1374792.79      6864170.76      1374860.98      6863835.83
      1374811.93      6863612.96
#Sta/Elev= 30
  4658.2 2138.31  4695.5 2136.94  4712.0 2135.89  4773.3 2134.28  4783.5 2133.55
  4791.6 2130.78  4796.7 2131.19  4814.1 2128.69  4834.5 2126.64  4847.3 2125.00
  4854.9 2123.20  4882.5 2119.68  4892.7 2118.50  4926.4 2116.95  4943.3 2116.49
  4987.6 2116.39  4993.9 2116.11  5000.1 2115.26  5000.6 2114.76  5006.9 2114.76
  5007.4 2115.26  5008.8 2115.68  5018.3 2115.27  5035.8 2116.06  5047.5 2116.94
  5052.6 2116.58  5079.7 2121.00  5151.4 2129.91  5202.6 2129.34  5228.2 2129.57
#Mann=5,-1,0
  4658.2    0.07       0  4882.5   0.035       0  5000.1   0.035       0
  5007.4   0.035       0  5035.8    0.07       0
Bank Sta=5000.1,5007.4
Exp/Cntr=0.3,0.1

Type RM Length L Ch R = 1,13769,490,490,490
BEGIN DESCRIPTION:
Sweetwater Creek Trib 27 T8 26.0
END DESCRIPTION:
XS GIS Cut Line= 3
      1375105.00      6863987.99      1375130.00      6863787.95
      1375105.00      6863638.02
#Sta/Elev= 30
  4798.4 2128.46  4808.5 2128.84  4818.5 2128.56  4836.2 2126.61  4841.2 2127.83
  4858.9 2124.51  4879.0 2121.88  4889.1 2121.63  4909.2 2120.37  4916.8 2119.29
  4921.9 2119.65  4939.5 2117.33  4949.6 2116.83  4959.6 2115.03  4969.7 2113.78
  4979.8 2113.25  5020.2 2113.55  5035.8 2113.23  5036.9 2113.22  5037.4 2112.72
  5043.7 2112.72  5044.2 2113.22  5050.6 2113.90  5063.3 2116.08  5081.1 2120.43
  5111.5 2123.11  5119.1 2124.78  5124.1 2124.60  5141.9 2127.95  5152.0 2128.31
#Mann=4,-1,0
  4798.4    0.07       0  5035.8   0.035       0  5036.9    0.07       0
  5044.2   0.035       0
Bank Sta=5036.9,5044.2
Exp/Cntr=0.3,0.1

Type RM Length L Ch R = 1,13279,474,474,474
BEGIN DESCRIPTION:
Sweetwater Creek Trib 27 T8 25.0
END DESCRIPTION:
XS GIS Cut Line= 3
      1375304.99      6864238.01      1375411.48      6864094.76
      1375504.98      6863938.03
#Sta/Elev= 30
  4821.5 2127.50  4843.4 2126.25  4864.3 2123.79  4871.4 2123.47  4885.1 2120.82
  4921.2 2118.63  4943.6 2111.05  4958.2 2109.56  4964.4 2109.68  4975.4 2109.03
  4975.9 2108.53  4982.2 2108.53  4982.7 2109.03  4985.2 2109.60  5007.9 2109.26
  5015.2 2109.67  5021.0 2110.69  5030.7 2110.43  5066.1 2114.52  5089.1 2116.72
  5102.0 2118.65  5110.5 2118.47  5116.4 2119.61  5124.3 2119.60  5147.5 2123.81
  5153.3 2125.30  5159.2 2125.94  5168.9 2125.52  5174.7 2126.00  5182.5 2125.72
#Mann=4,-1,0
  4821.5    0.07       0  4975.4    0.07       0  4982.7    0.07       0
  5102.0   0.035       0
Bank Sta=4975.4,4982.7
Exp/Cntr=0.3,0.1

Type RM Length L Ch R = 1,12805,495,495,495
BEGIN DESCRIPTION:
Sweetwater Creek Trib 27 T8 24.0
END DESCRIPTION:
XS GIS Cut Line= 3
      1375868.25      6864390.76      1375832.24      6864137.92
      1375662.54      6863927.26
#Sta/Elev= 30
  4744.6 2124.05  4818.1 2123.52  4828.2 2122.60  4838.3 2120.59  4868.6 2119.11
  4873.8 2117.06  4909.0 2113.76  4919.1 2114.07  4939.3 2111.17  4944.7 2109.47
  4949.7 2106.79  4955.9 2106.61  4956.4 2106.11  4963.2 2106.61  5000.0 2106.93
  5012.7 2107.91  5019.3 2107.01  5040.1 2107.30  5068.9 2111.03  5089.8 2115.20
  5132.9 2118.35  5168.1 2119.88  5190.5 2119.30  5204.9 2119.46  5211.3 2120.34
  5218.2 2119.62  5237.3 2120.25  5246.5 2120.84  5254.5 2122.89  5270.5 2124.05
#Mann=4,-1,0
  4744.6    0.07       0  4955.9    0.07       0  4963.2    0.07       0
  5237.3   0.035       0
Bank Sta=4955.9,4963.2
Exp/Cntr=0.3,0.1

Type RM Length L Ch R = 1,12310,496,496,496
BEGIN DESCRIPTION:
Sweetwater Creek Trib 27 T8 23.0
END DESCRIPTION:
XS GIS Cut Line= 3
      1376055.03      6864387.97      1376241.35      6864224.74
      1376355.02      6864137.98
#Sta/Elev= 30
  4752.3 2120.58  4808.7 2118.83  4830.5 2117.08  4844.8 2116.95  4858.6 2115.49
  4872.3 2115.00  4900.8 2112.37  4915.0 2109.00  4922.6 2108.86  4929.3 2106.66
  4943.5 2105.08  4951.1 2104.37  4972.0 2104.81  4973.3 2104.14  4973.8 2103.64
  4983.4 2103.64  4983.9 2104.14  4986.2 2105.01  4999.1 2104.19  5006.9 2104.77
  5029.7 2104.21  5035.9 2104.78  5042.3 2104.55  5071.3 2107.30  5093.0 2110.16
  5106.6 2111.52  5114.9 2113.74  5121.2 2117.83  5142.7 2120.42  5143.0 2120.42
#Mann=5,-1,0
  4752.3    0.07       0  4973.3    0.07       0  4983.9    0.07       0
  5093.0   0.035       0  5142.7    0.07       0
Bank Sta=4973.3,4983.9
Exp/Cntr=0.3,0.1

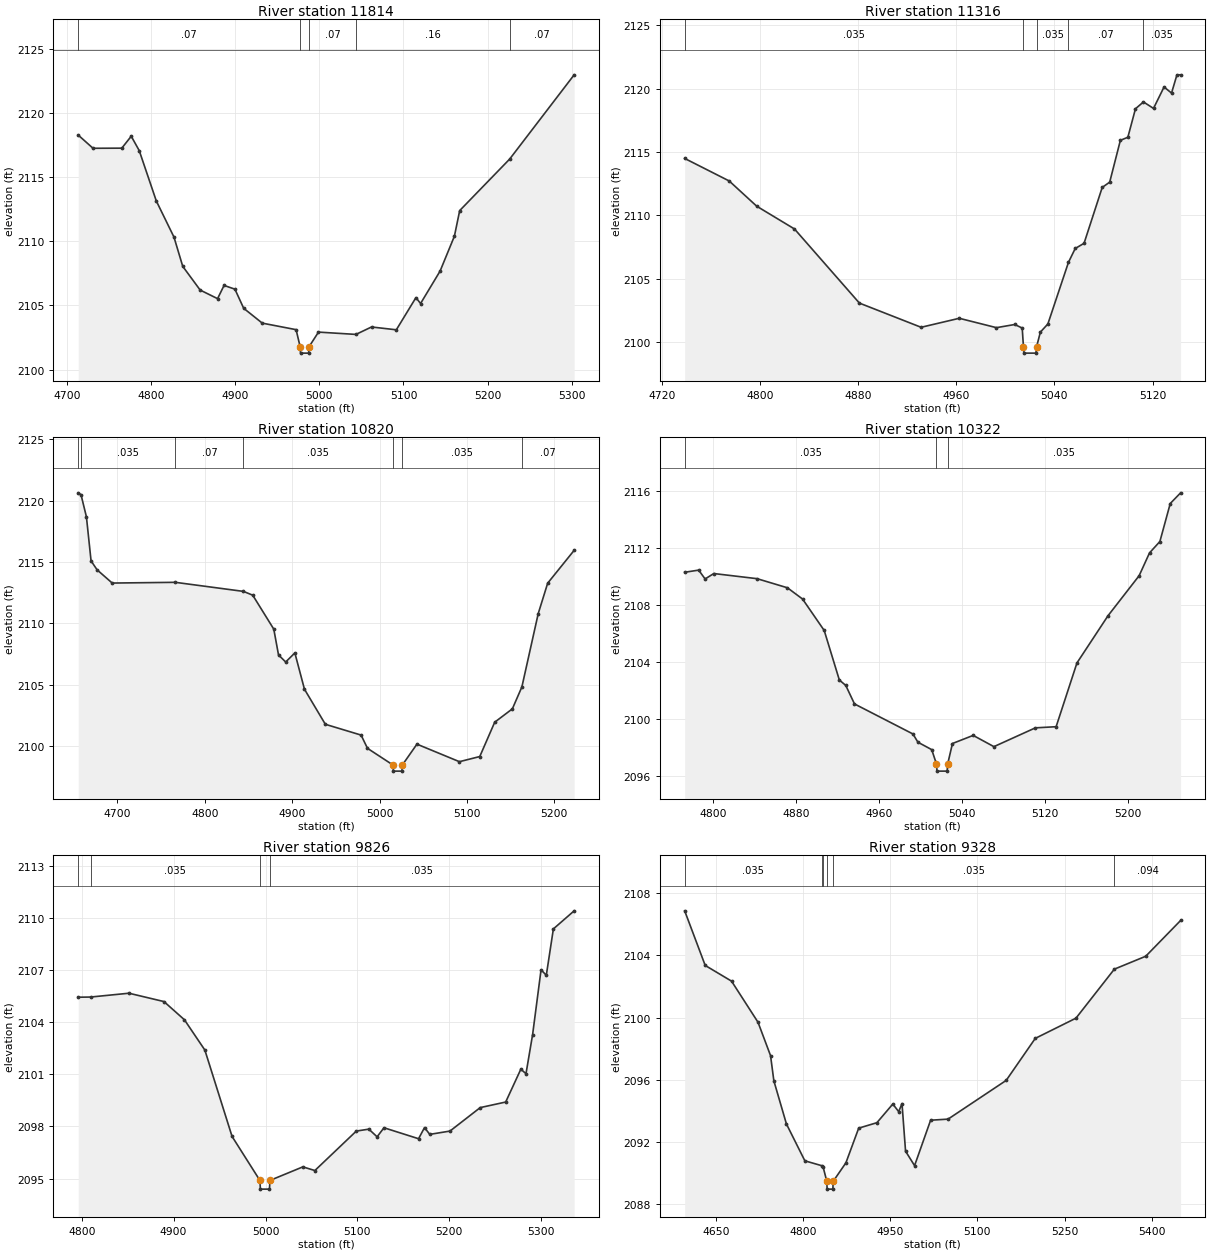
Type RM Length L Ch R = 1,11814,498,498,498
BEGIN DESCRIPTION:
Sweetwater Creek Trib 27 T8 22.0
END DESCRIPTION:
XS GIS Cut Line= 3
      1376304.96      6864638.01      1376581.92      6864564.69
      1376704.99      6864288.03
#Sta/Elev= 30
  4713.5 2118.29  4731.1 2117.26  4765.3 2117.27  4776.5 2118.20  4786.0 2117.08
  4806.3 2113.15  4827.3 2110.33  4837.7 2108.05  4858.4 2106.20  4879.1 2105.53
  4886.8 2106.56  4899.7 2106.27  4910.1 2104.78  4932.2 2103.62  4972.4 2103.11
  4977.2 2101.78  4977.7 2101.28  4987.3 2101.28  4987.8 2101.78  4999.0 2102.92
  5043.5 2102.74  5062.0 2103.32  5091.5 2103.10  5114.8 2105.61  5120.3 2105.15
  5143.5 2107.68  5160.5 2110.40  5166.8 2112.40  5226.2 2116.42  5302.8 2122.99
#Mann=5,-1,0
  4713.5    0.07       0  4977.2    0.07       0  4987.8    0.07       0
  5043.5    0.16       0  5226.2    0.07       0
Bank Sta=4977.2,4987.8
Exp/Cntr=0.3,0.1

Type RM Length L Ch R = 1,11316,496,496,496
BEGIN DESCRIPTION:
Sweetwater Creek Trib 27 T8 21.0
END DESCRIPTION:
XS GIS Cut Line= 3
      1376754.98      6864888.01      1376988.55      6864770.87
      1377104.98      6864688.02
#Sta/Elev= 30
  4738.7 2114.50  4775.0 2112.72  4797.4 2110.73  4828.2 2108.93  4881.1 2103.08
  4931.4 2101.17  4962.5 2101.88  4992.8 2101.14  5007.7 2101.39  5013.8 2101.11
  5014.8 2099.63  5015.3 2099.13  5025.0 2099.13  5025.5 2099.63  5028.6 2100.79
  5034.7 2101.43  5051.5 2106.30  5057.0 2107.39  5064.2 2107.80  5079.0 2112.21
  5085.1 2112.63  5093.8 2115.93  5099.9 2116.17  5106.1 2118.42  5112.6 2118.96
  5120.8 2118.45  5129.4 2120.14  5135.5 2119.66  5139.9 2121.10  5142.9 2121.10
#Mann=5,-1,0
  4738.7   0.035       0  5014.8   0.035       0  5025.5   0.035       0
  5051.5    0.07       0  5112.6   0.035       0
Bank Sta=5014.8,5025.5
Exp/Cntr=0.3,0.1

Type RM Length L Ch R = 1,10820,498,498,498
BEGIN DESCRIPTION:
Sweetwater Creek Trib 27 T8 20.0
END DESCRIPTION:
XS GIS Cut Line= 3
      1376905.00      6865288.00      1377224.59      6865158.57
      1377255.01      6864937.96
#Sta/Elev= 30
  4655.2 2120.64  4658.4 2120.49  4664.6 2118.68  4669.9 2115.09  4676.8 2114.36
  4694.1 2113.28  4766.3 2113.34  4844.3 2112.60  4854.9 2112.29  4879.0 2109.52
  4884.4 2107.42  4892.6 2106.84  4903.1 2107.58  4914.1 2104.62  4938.0 2101.76
  4978.9 2100.88  4986.2 2099.80  5015.4 2098.44  5015.9 2097.94  5025.6 2097.94
  5026.1 2098.44  5042.8 2100.14  5091.4 2098.71  5114.7 2099.13  5131.8 2101.93
  5152.0 2103.02  5162.9 2104.81  5181.6 2110.79  5192.4 2113.27  5222.7 2115.95
#Mann=7,-1,0
  4655.2    0.07       0  4658.4   0.035       0  4766.3    0.07       0
  4844.3   0.035       0  5015.4   0.035       0  5026.1   0.035       0
  5162.9    0.07       0
Bank Sta=5015.4,5026.1
Exp/Cntr=0.3,0.1

Type RM Length L Ch R = 1,10322,496,496,496
BEGIN DESCRIPTION:
Sweetwater Creek Trib 27 T8 19.0
END DESCRIPTION:
XS GIS Cut Line= 3
      1377560.36      6865421.67      1377695.72      6865238.45
      1377705.00      6864988.02
#Sta/Elev= 30
  4772.2 2110.32  4785.7 2110.47  4791.9 2109.85  4800.3 2110.23  4842.0 2109.87
  4871.3 2109.23  4885.9 2108.44  4906.8 2106.23  4921.4 2102.75  4927.6 2102.37
  4936.0 2101.07  4992.4 2098.96  4997.2 2098.38  5010.5 2097.86  5015.1 2096.85
  5015.6 2096.35  5025.4 2096.35  5025.9 2096.85  5030.5 2098.29  5050.5 2098.86
  5070.5 2098.07  5110.5 2099.39  5130.5 2099.47  5150.6 2103.95  5180.6 2107.27
  5210.6 2110.08  5220.6 2111.68  5230.6 2112.48  5240.6 2115.15  5250.6 2115.90
#Mann=3,-1,0
  4772.2   0.035       0  5015.1   0.035       0  5025.9   0.035       0
Bank Sta=5015.1,5025.9
Exp/Cntr=0.3,0.1

Type RM Length L Ch R = 1,9826,498,498,498
BEGIN DESCRIPTION:
Sweetwater Creek Trib 27 T8 18.0
END DESCRIPTION:
XS GIS Cut Line= 3
      1378068.25      6865517.25      1378160.56      6865335.55
      1378004.98      6865037.97
#Sta/Elev= 30
  4796.2 2105.43  4809.6 2105.44  4851.4 2105.66  4889.5 2105.18  4911.8 2104.13
  4934.0 2102.39  4963.6 2097.42  4993.9 2094.89  4994.4 2094.39  5004.3 2094.39
  5004.8 2094.89  5040.6 2095.67  5053.7 2095.46  5098.8 2097.73  5112.4 2097.84
  5121.4 2097.40  5128.9 2097.92  5166.5 2097.29  5173.0 2097.93  5178.7 2097.54
  5200.7 2097.73  5233.6 2099.08  5261.3 2099.40  5277.8 2101.29  5283.4 2101.03
  5290.6 2103.28  5299.8 2107.01  5305.5 2106.69  5313.2 2109.36  5335.8 2110.40
#Mann=4,-1,0
  4796.2    0.07       0  4809.6   0.035       0  4993.9   0.035       0
  5004.8   0.035       0
Bank Sta=4993.9,5004.8
Exp/Cntr=0.3,0.1

Type RM Length L Ch R = 1,9328,471,471,471
BEGIN DESCRIPTION:
Sweetwater Creek Trib 27 T8 17.0
END DESCRIPTION:
XS GIS Cut Line= 3
      1378805.01      6865838.02      1378605.17      6865487.60
      1378605.00      6865038.00
#Sta/Elev= 30
  4596.6 2106.87  4631.9 2103.36  4677.2 2102.35  4722.7 2099.71  4744.3 2097.56
  4750.0 2095.94  4771.6 2093.17  4803.3 2090.80  4833.0 2090.48  4834.5 2090.43
  4841.1 2089.48  4841.6 2088.98  4851.5 2088.98  4852.0 2089.48  4873.9 2090.67
  4895.9 2092.90  4927.2 2093.25  4954.6 2094.45  4964.7 2093.96  4970.4 2094.48
  4976.5 2091.42  4992.0 2090.49  5019.6 2093.41  5049.6 2093.48  5149.6 2095.97
  5199.6 2098.67  5269.6 2099.97  5335.6 2103.12  5389.6 2103.95  5449.6 2106.25
#Mann=6,-1,0
  4596.6   0.035       0  4833.0    0.07       0  4834.5   0.035       0
  4841.1   0.035       0  4852.0   0.035       0  5335.6   0.094       0
Bank Sta=4841.1,4852
Exp/Cntr=0.3,0.1

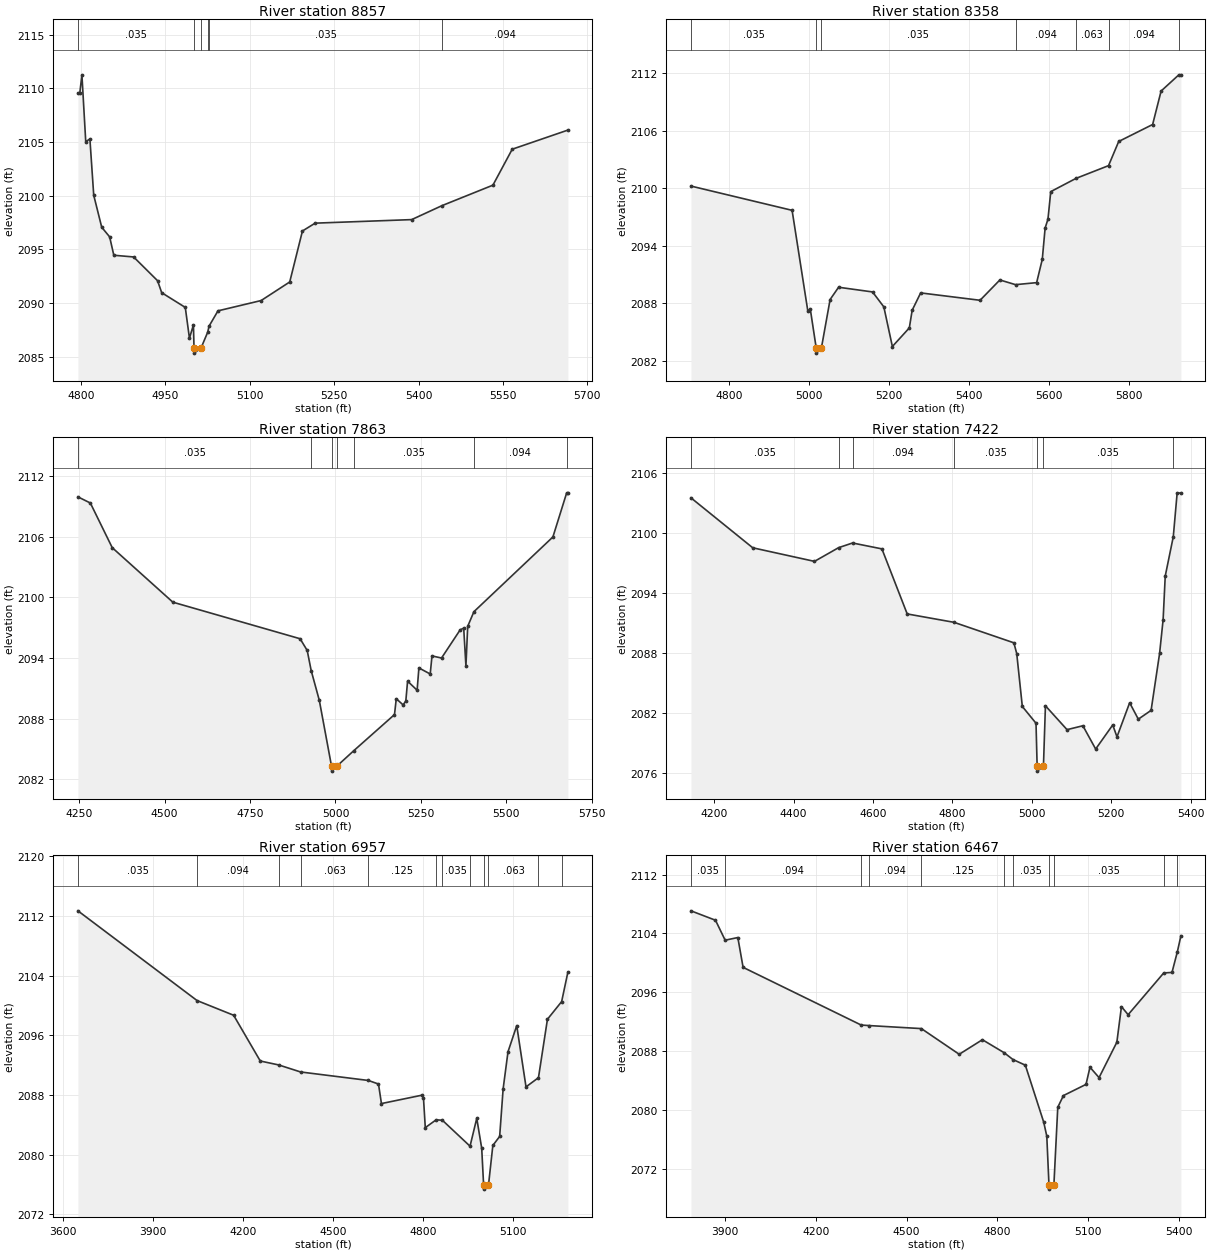
Type RM Length L Ch R = 1,8857,499,499,499
BEGIN DESCRIPTION:
Sweetwater Creek Trib 27 T8 16.0
END DESCRIPTION:
XS GIS Cut Line= 3
      1378904.98      6865738.02      1379044.31      6865587.23
      1378755.01      6864988.01
#Sta/Elev= 30
  4794.7 2109.58  4798.1 2109.58  4801.8 2111.26  4808.6 2105.04  4816.0 2105.28
  4822.8 2100.04  4837.0 2097.06  4851.1 2096.16  4858.5 2094.45  4893.7 2094.29
  4936.2 2092.08  4943.6 2090.96  4985.5 2089.59  4992.9 2086.72  5000.0 2087.96
  5001.0 2085.83  5001.5 2085.33  5013.7 2085.83  5025.4 2087.29  5027.7 2087.84
  5043.6 2089.27  5120.3 2090.23  5171.1 2091.96  5193.7 2096.71  5216.3 2097.44
  5387.8 2097.77  5441.6 2099.07  5532.2 2100.98  5566.5 2104.33  5665.4 2106.11
#Mann=6,-1,0
  4794.7   0.035       0  5001.0   0.035       0  5013.7   0.035       0
  5025.4    0.07       0  5027.7   0.035       0  5441.6   0.094       0
Bank Sta=5001,5013.7
Exp/Cntr=0.3,0.1

Type RM Length L Ch R = 1,8358,495,495,495
BEGIN DESCRIPTION:
Sweetwater Creek Trib 27 T8 15.0
END DESCRIPTION:
XS GIS Cut Line= 3
      1379405.00      6865638.00      1379448.94      6865345.48
      1380104.99      6864688.01
#Sta/Elev= 30
  4704.2 2100.22  4957.0 2097.69  4996.2 2087.22  5002.5 2087.39  5017.4 2083.30
  5017.9 2082.80  5030.1 2083.30  5052.0 2088.39  5073.2 2089.67  5158.1 2089.18
  5186.3 2087.62  5207.6 2083.49  5250.0 2085.43  5257.1 2087.27  5278.3 2089.08
  5426.8 2088.31  5476.3 2090.43  5515.4 2089.94  5568.2 2090.15  5582.3 2092.58
  5589.4 2095.84  5596.5 2096.77  5603.5 2099.64  5666.5 2101.02  5747.9 2102.35
  5773.3 2104.87  5858.1 2106.64  5879.3 2110.13  5923.1 2111.80  5928.8 2111.82
#Mann=7,-1,0
  4704.2   0.035       0  5017.4   0.035       0  5030.1   0.035       0
  5515.4   0.094       0  5666.5   0.063       0  5747.9   0.094       0
  5923.1   0.035       0
Bank Sta=5017.4,5030.1
Exp/Cntr=0.3,0.1

Type RM Length L Ch R = 1,7863,441,441,441
BEGIN DESCRIPTION:
Sweetwater Creek Trib 27 T8 14.0
END DESCRIPTION:
XS GIS Cut Line= 3
      1379454.98      6866038.03      1379910.18      6865437.57
      1380105.13      6864786.01
#Sta/Elev= 30
  4246.5 2109.95  4282.9 2109.34  4346.9 2104.92  4524.3 2099.52  4896.6 2095.90
  4917.4 2094.74  4929.0 2092.75  4952.8 2089.80  4988.5 2083.29  4989.0 2082.79
  5004.4 2083.29  5053.2 2084.80  5172.8 2088.39  5178.0 2089.96  5197.9 2089.35
  5205.9 2089.73  5211.1 2091.70  5239.0 2090.80  5244.2 2093.01  5277.3 2092.41
  5282.5 2094.20  5310.4 2093.99  5364.9 2096.78  5375.3 2096.95  5381.8 2093.20
  5387.0 2097.13  5405.2 2098.58  5636.3 2105.98  5676.6 2110.35  5680.1 2110.35
#Mann=7,-1,0
  4246.5   0.035       0  4929.0   0.063       0  4988.5   0.063       0
  5004.4   0.063       0  5053.2   0.035       0  5405.2   0.094       0
  5676.6   0.035       0
Bank Sta=4988.5,5004.4
Exp/Cntr=0.3,0.1

Type RM Length L Ch R = 1,7422,465,465,465
BEGIN DESCRIPTION:
Sweetwater Creek Trib 27 T8 13.0
END DESCRIPTION:
XS GIS Cut Line= 3
      1379704.97      6866038.03      1380318.69      6865437.86
      1380455.01      6865087.98
#Sta/Elev= 30
  4141.6 2103.50  4297.2 2098.50  4452.7 2097.14  4513.3 2098.51  4548.6 2098.98
  4622.5 2098.39  4686.2 2091.88  4804.2 2091.04  4954.8 2088.99  4962.0 2087.92
  4976.1 2082.62  5010.6 2080.94  5013.4 2076.65  5013.9 2076.15  5029.3 2076.65
  5034.3 2082.69  5088.7 2080.30  5128.6 2080.69  5160.8 2078.36  5203.8 2080.77
  5214.5 2079.58  5246.4 2082.99  5268.2 2081.35  5300.4 2082.23  5321.8 2087.93
  5330.7 2091.31  5336.0 2095.67  5356.3 2099.61  5365.9 2103.94  5375.5 2104.00
#Mann=7,-1,0
  4141.6   0.035       0  4513.3   0.125       0  4548.6   0.094       0
  4804.2   0.035       0  5013.4   0.035       0  5029.3   0.035       0
  5356.3   0.063       0
Bank Sta=5013.4,5029.3
Exp/Cntr=0.3,0.1

Type RM Length L Ch R = 1,6957,490,490,490
BEGIN DESCRIPTION:
Sweetwater Creek Trib 27 T8 12.0
END DESCRIPTION:
XS GIS Cut Line= 3
      1379505.04      6866237.98      1380706.02      6865622.29
      1380955.01      6865487.99
#Sta/Elev= 30
  3650.4 2112.71  4047.4 2100.67  4169.2 2098.70  4258.0 2092.56  4319.6 2092.03
  4392.3 2091.09  4618.1 2089.95  4651.9 2089.47  4661.7 2086.85  4796.1 2087.97
  4801.7 2087.64  4807.8 2083.62  4844.0 2084.67  4864.8 2084.61  4956.9 2081.13
  4979.3 2084.87  4995.8 2080.85  5002.2 2075.87  5002.7 2075.37  5018.3 2075.87
  5032.9 2081.23  5055.6 2082.44  5067.2 2088.83  5083.4 2093.80  5112.5 2097.31
  5143.4 2089.09  5184.9 2090.32  5214.8 2098.16  5262.1 2100.53  5282.9 2104.48
#Mann=12,-1,0
  3650.4   0.035       0  4047.4   0.094       0  4319.6   0.125       0
  4392.3   0.063       0  4618.1   0.125       0  4844.0   0.063       0
  4864.8   0.035       0  4956.9   0.063       0  5002.2   0.063       0
  5018.3   0.063       0  5184.9   0.035       0  5262.1   0.063       0
Bank Sta=5002.2,5018.3
Exp/Cntr=0.3,0.1

Type RM Length L Ch R = 1,6467,498,498,498
BEGIN DESCRIPTION:
Sweetwater Creek Trib 27 T8 11.0
END DESCRIPTION:
XS GIS Cut Line= 3
      1379705.01      6866238.00      1380901.45      6866039.47
      1381105.02      6865687.96
#Sta/Elev= 30
  3787.2 2107.07  3868.3 2105.79  3900.2 2103.08  3942.1 2103.44  3959.5 2099.39
  4349.8 2091.55  4376.2 2091.48  4548.6 2091.07  4673.6 2087.58  4750.2 2089.56
  4822.2 2087.79  4851.1 2086.87  4892.1 2086.10  4952.9 2078.35  4963.0 2076.46
  4970.3 2069.76  4970.8 2069.26  4986.4 2069.76  4999.3 2080.38  5018.0 2081.97
  5092.6 2083.49  5105.7 2085.82  5135.7 2084.41  5194.5 2089.22  5209.7 2094.05
  5231.8 2092.96  5349.4 2098.63  5376.7 2098.70  5394.4 2101.50  5406.2 2103.68
#Mann=11,-1,0
  3787.2   0.035       0  3900.2   0.094       0  4349.8   0.125       0
  4376.2   0.094       0  4548.6   0.125       0  4822.2   0.094       0
  4851.1   0.035       0  4970.3   0.035       0  4986.4   0.035       0
  5349.4   0.063       0  5394.4   0.094       0
Bank Sta=4970.3,4986.4
Exp/Cntr=0.3,0.1

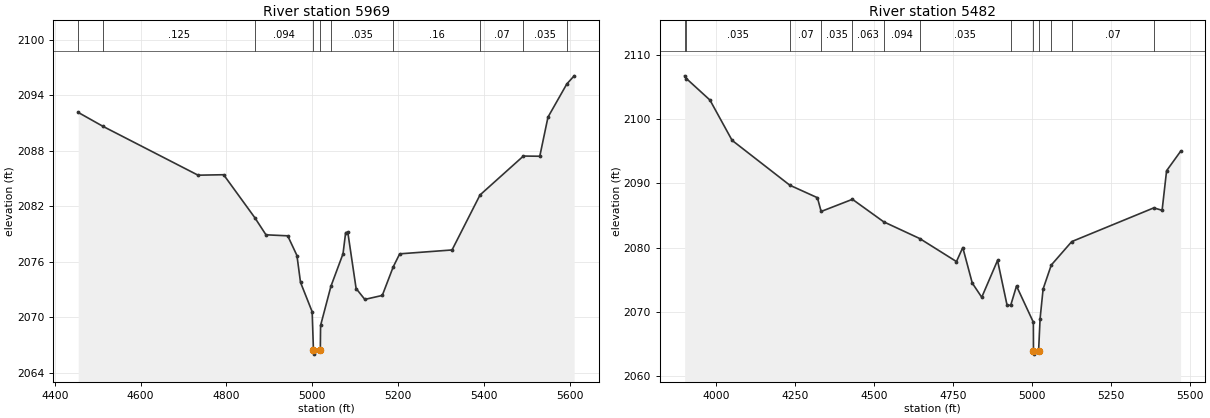
Type RM Length L Ch R = 1,5969,487,487,487
BEGIN DESCRIPTION:
Sweetwater Creek Trib 27 T8 10.0
END DESCRIPTION:
XS GIS Cut Line= 3
      1380405.02      6866188.01      1380854.24      6866497.13
      1381455.00      6866388.00
#Sta/Elev= 30
  4454.7 2092.16  4513.0 2090.64  4734.0 2085.37  4793.6 2085.42  4866.5 2080.76
  4892.3 2078.92  4943.0 2078.81  4964.5 2076.68  4972.8 2073.78  5000.0 2070.59
  5002.9 2066.51  5003.4 2066.01  5019.0 2066.51  5019.6 2069.11  5043.7 2073.35
  5071.9 2076.87  5078.0 2079.16  5083.1 2079.18  5102.4 2073.11  5122.7 2071.93
  5163.4 2072.36  5188.9 2075.45  5204.0 2076.86  5326.0 2077.28  5391.2 2083.23
  5492.3 2087.44  5530.5 2087.42  5549.6 2091.65  5593.5 2095.24  5610.6 2096.12
#Mann=10,-1,0
  4454.7   0.094       0  4513.0   0.125       0  4866.5   0.094       0
  5002.9    0.07       0  5019.0   0.094       0  5043.7   0.035       0
  5188.9    0.16       0  5391.2    0.07       0  5492.3   0.035       0
  5593.5   0.094       0
Bank Sta=5002.9,5019
Exp/Cntr=0.3,0.1

Type RM Length L Ch R = 1,5482,481,481,481
BEGIN DESCRIPTION:
Sweetwater Creek Trib 27 T8 9.0
END DESCRIPTION:
XS GIS Cut Line= 3
      1380004.97      6866788.00      1381104.76      6866783.47
      1381504.98      6866538.01
#Sta/Elev= 30
  3900.2 2106.74  3905.7 2106.31  3980.2 2102.97  4050.2 2096.71  4233.0 2089.73
  4320.2 2087.79  4332.0 2085.65  4431.0 2087.54  4530.0 2084.04  4644.0 2081.44
  4760.2 2077.86  4780.2 2080.04  4810.2 2074.52  4840.2 2072.31  4890.2 2078.04
  4920.2 2071.11  4931.8 2071.05  4950.2 2074.06  5003.5 2068.43  5003.9 2063.97
  5004.4 2063.47  5020.1 2063.97  5024.8 2068.97  5034.4 2073.60  5060.2 2077.32
  5125.1 2080.97  5384.7 2086.21  5410.9 2085.83  5425.1 2091.98  5469.5 2095.01
#Mann=13,-1,0
  3900.2   0.063       0  3905.7   0.035       0  4233.0    0.07       0
  4332.0   0.035       0  4431.0   0.063       0  4530.0   0.094       0
  4644.0   0.035       0  4931.8    0.07       0  5003.9    0.07       0
  5020.1    0.07       0  5060.2    0.16       0  5125.1    0.07       0
  5384.7   0.035       0
Bank Sta=5003.9,5020.1
Exp/Cntr=0.3,0.1