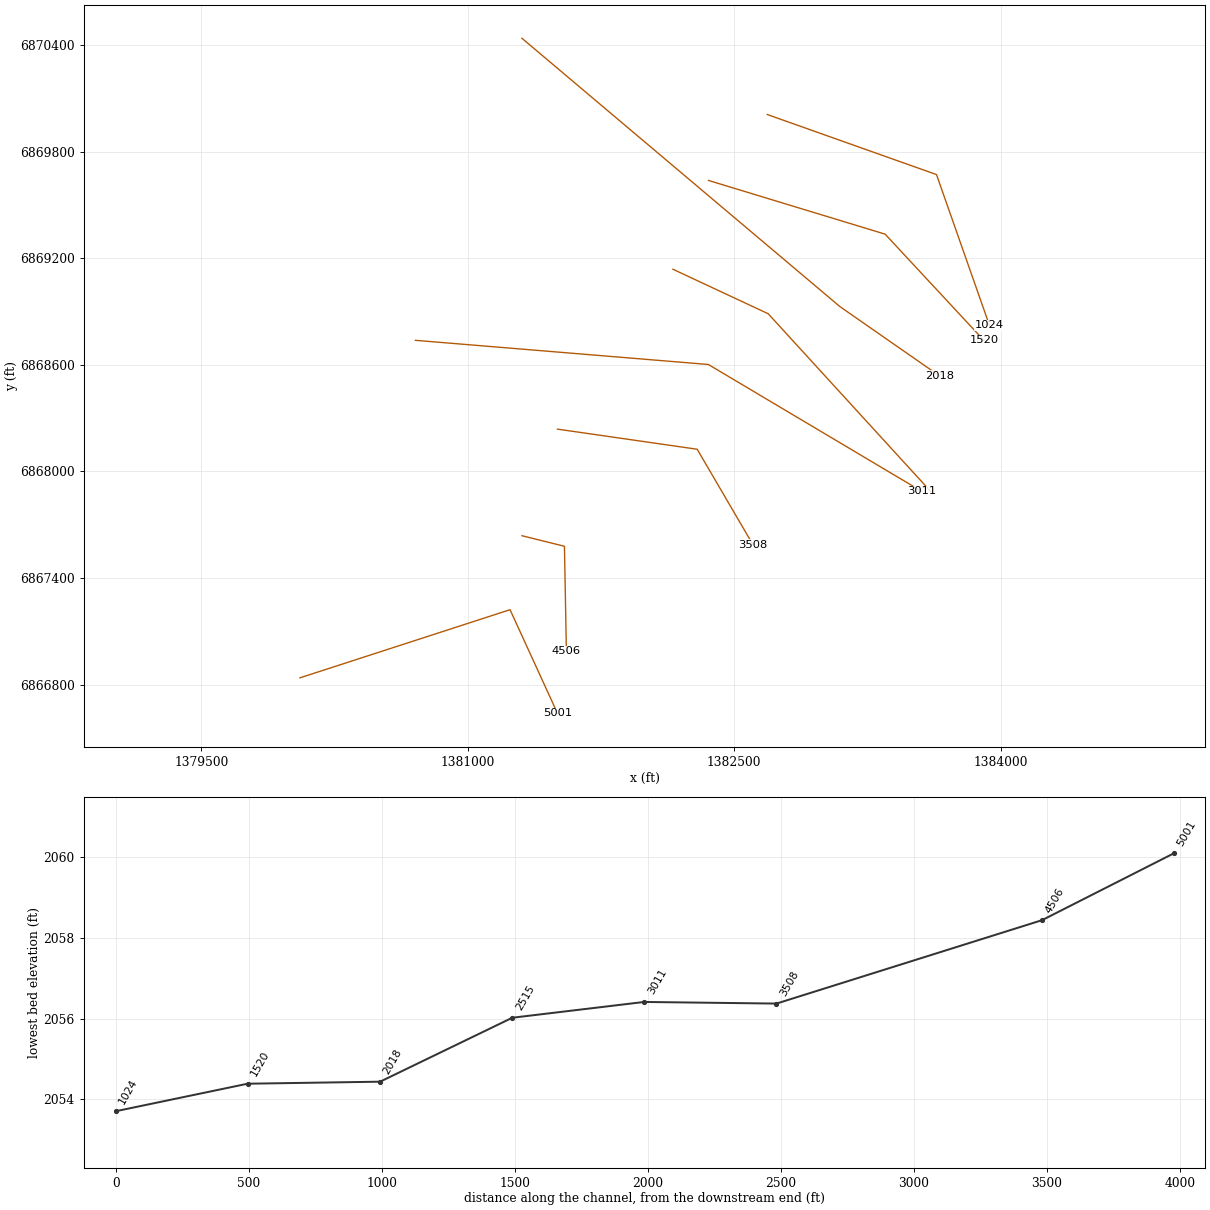
HEC-RAS study Sweetwater Creek Trib 27 T8.prj: Sweetwater Creek Trib 27 T8 Base Level Engineering

--- Sweetwater Creek Trib 27 T8.g01 (geometry) --- (continued)

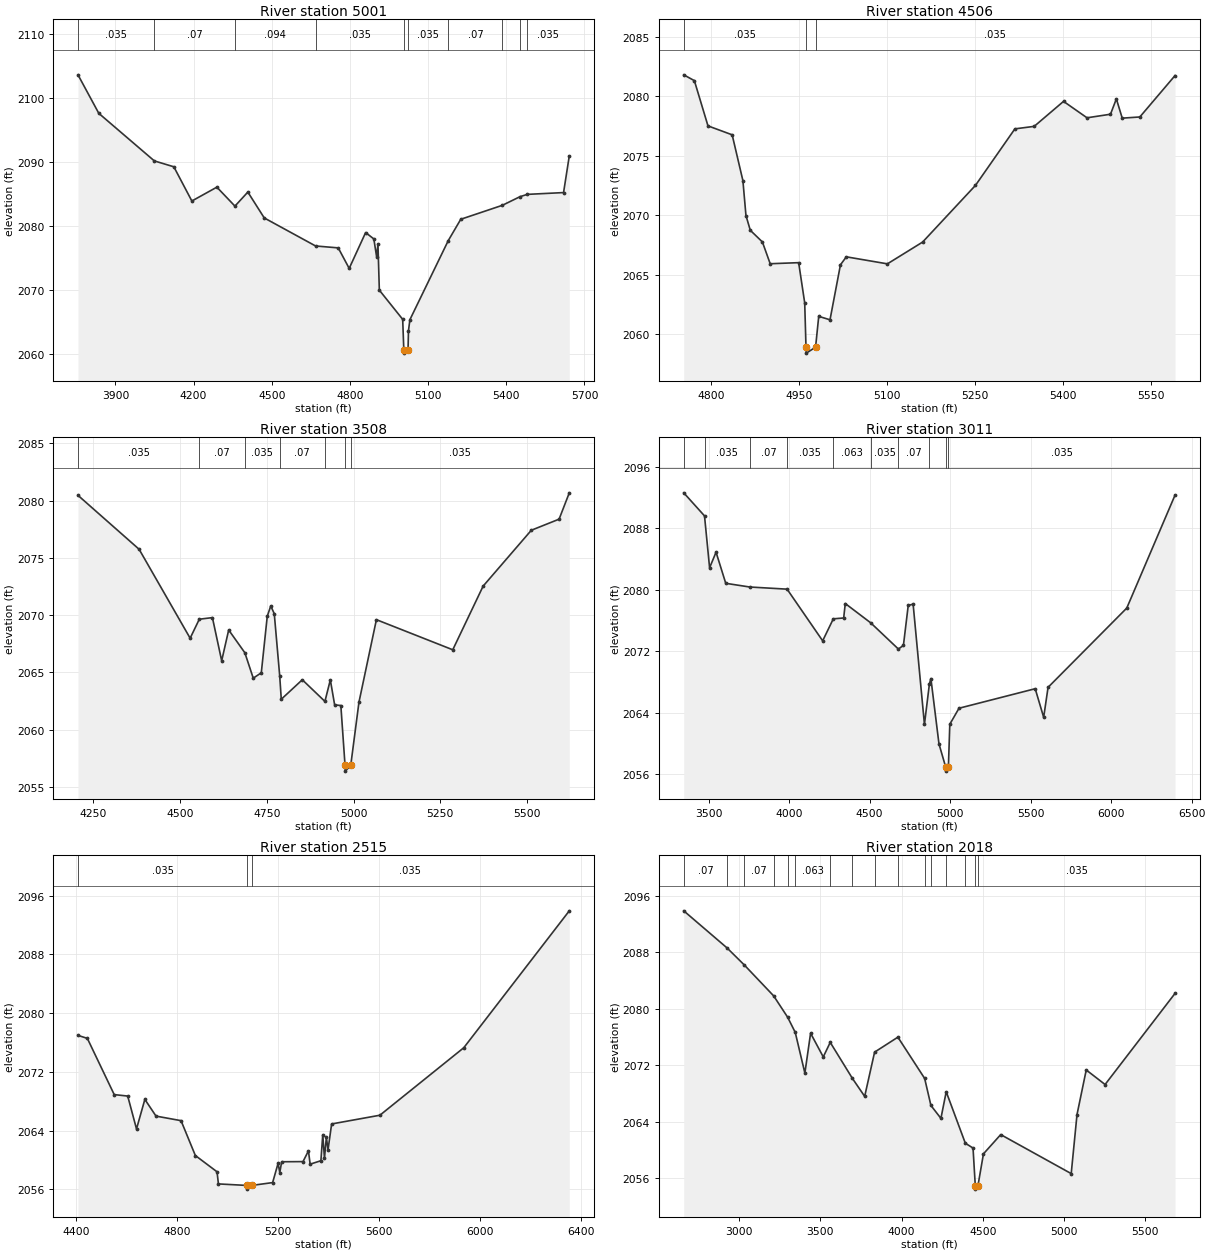
Type RM Length L Ch R = 1,5001,495,495,495
BEGIN DESCRIPTION:
Sweetwater Creek Trib 27 T8 8.0
END DESCRIPTION:
XS GIS Cut Line= 3
      1380055.00      6866838.00      1381237.88      6867221.52
      1381505.02      6866637.96
#Sta/Elev= 30
  3756.5 2103.66  3836.4 2097.63  4049.5 2090.18  4124.3 2089.26  4193.5 2083.90
  4289.4 2086.07  4358.8 2083.10  4408.3 2085.30  4471.3 2081.25  4668.2 2076.86
  4755.2 2076.56  4797.2 2073.35  4860.3 2078.96  4891.8 2077.96  4902.3 2075.21
  4907.6 2077.13  4912.9 2069.94  5002.5 2065.37  5006.8 2060.58  5007.3 2060.08
  5023.0 2060.58  5024.7 2063.59  5030.2 2065.32  5177.5 2077.71  5225.3 2081.04
  5385.1 2083.23  5452.2 2084.57  5480.5 2084.94  5619.8 2085.22  5641.8 2090.97
#Mann=10,-1,0
  3756.5   0.035       0  4049.5    0.07       0  4358.8   0.094       0
  4668.2   0.035       0  5006.8   0.035       0  5023.0   0.035       0
  5177.5    0.07       0  5385.1   0.035       0  5452.2    0.07       0
  5480.5   0.035       0
Bank Sta=5006.8,5023
Exp/Cntr=0.3,0.1

Type RM Length L Ch R = 1,4506,998,998,998
BEGIN DESCRIPTION:
Sweetwater Creek Trib 27 T8 7.0
END DESCRIPTION:
XS GIS Cut Line= 3
      1381304.96      6867638.01      1381544.09      6867578.59
      1381555.00      6866987.99
#Sta/Elev= 30
  4753.6 2081.81  4771.7 2081.32  4794.9 2077.52  4836.1 2076.77  4854.4 2072.92
  4859.6 2069.99  4867.0 2068.75  4887.6 2067.77  4900.9 2065.94  4949.4 2066.03
  4959.7 2062.65  4961.9 2058.93  4962.4 2058.43  4978.2 2058.93  4983.6 2061.52
  5002.8 2061.23  5020.6 2065.85  5030.6 2066.52  5100.6 2065.93  5160.6 2067.76
  5250.6 2072.52  5317.8 2077.27  5350.7 2077.48  5400.7 2079.58  5440.7 2078.20
  5480.7 2078.50  5490.7 2079.79  5500.7 2078.17  5530.7 2078.27  5590.7 2081.75
#Mann=3,-1,0
  4753.6   0.035       0  4961.9   0.035       0  4978.2   0.035       0
Bank Sta=4961.9,4978.2
Exp/Cntr=0.3,0.1

Type RM Length L Ch R = 1,3508,497,497,497
BEGIN DESCRIPTION:
Sweetwater Creek Trib 27 T8 5.0
END DESCRIPTION:
XS GIS Cut Line= 3
      1381504.98      6868238.00      1382291.28      6868124.83
      1382605.01      6867587.98
#Sta/Elev= 30
  4205.6 2080.46  4381.8 2075.75  4528.9 2067.98  4555.3 2069.64  4593.1 2069.78
  4619.8 2066.01  4640.0 2068.70  4686.6 2066.71  4710.8 2064.49  4734.0 2064.96
  4751.2 2069.90  4761.3 2070.80  4771.4 2070.12  4787.0 2064.71  4791.6 2062.65
  4852.2 2064.35  4917.4 2062.46  4933.0 2064.34  4945.4 2062.16  4963.3 2062.10
  4975.4 2056.87  4975.9 2056.37  4991.8 2056.87  5015.5 2062.39  5065.8 2069.60
  5285.9 2066.97  5373.4 2072.53  5512.3 2077.41  5592.4 2078.38  5621.8 2080.68
#Mann=7,-1,0
  4205.6   0.035       0  4555.3    0.07       0  4686.6   0.035       0
  4787.0    0.07       0  4917.4   0.035       0  4975.4   0.035       0
  4991.8   0.035       0
Bank Sta=4975.4,4991.8
Exp/Cntr=0.3,0.1

Type RM Length L Ch R = 1,3011,496,496,496
BEGIN DESCRIPTION:
Sweetwater Creek Trib 27 T8 4.0
END DESCRIPTION:
XS GIS Cut Line= 3
      1380704.98      6868738.00      1382354.18      6868601.98
      1383554.96      6867888.03
#Sta/Elev= 30
  3345.2 2092.61  3474.2 2089.61  3505.8 2082.86  3545.9 2084.89  3606.1 2080.84
  3754.9 2080.36  3987.1 2080.08  4208.1 2073.36  4274.3 2076.22  4338.6 2076.33
  4348.6 2078.21  4506.5 2075.70  4678.5 2072.29  4709.8 2072.77  4739.6 2077.96
  4770.0 2078.13  4840.3 2062.49  4871.2 2067.75  4880.4 2068.45  4930.6 2059.95
  4972.6 2056.91  4973.1 2056.41  4989.0 2056.91  4997.9 2062.51  5055.0 2064.59
  5528.3 2067.13  5580.9 2063.41  5608.2 2067.31  6097.1 2077.62  6397.0 2092.32
#Mann=10,-1,0
  3345.2    0.07       0  3474.2   0.035       0  3754.9    0.07       0
  3987.1   0.035       0  4274.3   0.063       0  4506.5   0.035       0
  4678.5    0.07       0  4871.2   0.035       0  4972.6   0.035       0
  4989.0   0.035       0
Bank Sta=4972.6,4989
Exp/Cntr=0.3,0.1

Type RM Length L Ch R = 1,2515,497,497,497
BEGIN DESCRIPTION:
Sweetwater Creek Trib 27 T8 3.0
END DESCRIPTION:
XS GIS Cut Line= 3
      1382154.98      6869138.01      1382691.08      6868887.60
      1383604.99      6867888.01
#Sta/Elev= 30
  4408.3 2076.97  4445.4 2076.56  4551.8 2068.90  4605.3 2068.70  4640.1 2064.22
  4673.2 2068.25  4717.4 2065.97  4816.5 2065.35  4873.2 2060.60  4959.1 2058.38
  4964.6 2056.73  5079.2 2056.52  5079.7 2056.02  5095.7 2056.52  5179.3 2056.91
  5200.9 2059.53  5207.7 2058.28  5215.1 2059.75  5299.6 2059.77  5321.2 2061.23
  5327.9 2059.42  5370.5 2059.89  5377.9 2063.44  5384.7 2060.23  5392.1 2063.07
  5398.8 2061.40  5413.0 2064.90  5604.2 2066.09  5936.6 2075.29  6354.4 2093.94
#Mann=3,-1,0
  4408.3   0.035       0  5079.2   0.035       0  5095.7   0.035       0
Bank Sta=5079.2,5095.7
Exp/Cntr=0.3,0.1

Type RM Length L Ch R = 1,2018,498,498,498
BEGIN DESCRIPTION:
Sweetwater Creek Trib 27 T8 2.0
END DESCRIPTION:
XS GIS Cut Line= 3
      1381305.03      6870437.98      1383094.22      6868928.32
      1383654.96      6868538.03
#Sta/Elev= 30
  2659.0 2093.89  2925.1 2088.64  3031.5 2086.22  3212.6 2081.83  3298.5 2078.81
  3345.3 2076.66  3404.6 2070.89  3439.8 2076.54  3517.8 2073.18  3560.7 2075.24
  3697.3 2070.13  3772.7 2067.59  3833.8 2073.86  3977.1 2075.98  4141.9 2070.13
  4180.5 2066.30  4242.0 2064.47  4274.6 2068.24  4392.2 2060.95  4439.7 2060.26
  4453.5 2054.94  4454.0 2054.44  4470.1 2054.94  4503.8 2059.44  4610.1 2062.17
  5044.0 2056.64  5079.7 2065.01  5136.5 2071.33  5252.5 2069.27  5683.2 2082.19
#Mann=16,-1,0
  2659.0    0.07       0  2925.1   0.035       0  3031.5    0.07       0
  3212.6    0.16       0  3298.5    0.07       0  3345.3   0.063       0
  3560.7   0.035       0  3697.3    0.07       0  3833.8   0.094       0
  3977.1   0.063       0  4141.9   0.035       0  4180.5   0.063       0
  4274.6    0.07       0  4392.2   0.035       0  4453.5   0.035       0
  4470.1   0.035       0
Bank Sta=4453.5,4470.1
Exp/Cntr=0.3,0.1

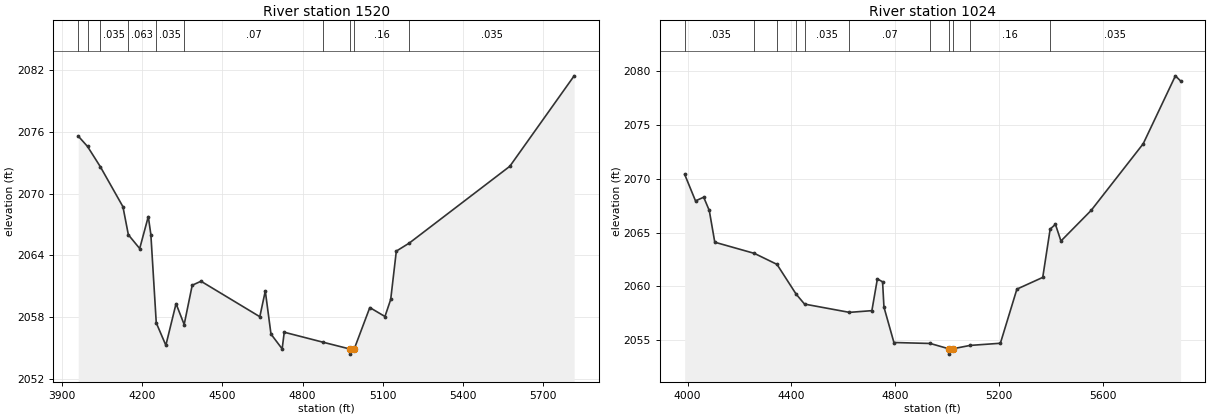
Type RM Length L Ch R = 1,1520,496,496,496
BEGIN DESCRIPTION:
Sweetwater Creek Trib 27 T8 1.0
END DESCRIPTION:
XS GIS Cut Line= 3
      1382354.98      6869638.01      1383349.23      6869335.68
      1383905.03      6868737.96
#Sta/Elev= 30
  3960.8 2075.60  3995.6 2074.59  4044.0 2072.60  4128.1 2068.73  4148.4 2066.00
  4190.8 2064.66  4223.0 2067.77  4232.6 2066.02  4252.8 2057.43  4288.7 2055.25
  4326.8 2059.30  4357.2 2057.27  4387.3 2061.09  4420.2 2061.48  4640.2 2058.03
  4660.7 2060.53  4682.0 2056.34  4723.8 2054.90  4731.6 2056.52  4875.1 2055.56
  4976.8 2054.89  4977.3 2054.39  4993.4 2054.89  5051.7 2058.92  5108.4 2058.05
  5129.9 2059.71  5150.9 2064.41  5199.3 2065.19  5575.5 2072.66  5816.2 2081.46
#Mann=10,-1,0
  3960.8   0.094       0  3995.6   0.063       0  4044.0   0.035       0
  4148.4   0.063       0  4252.8   0.035       0  4357.2    0.07       0
  4875.1    0.16       0  4976.8    0.07       0  4993.4    0.16       0
  5199.3   0.035       0
Bank Sta=4976.8,4993.4
Exp/Cntr=0.3,0.1

Type RM Length L Ch R = 1,1024,0,0,0
BEGIN DESCRIPTION:
Sweetwater Creek Trib 27 T8 0.1
END DESCRIPTION:
XS GIS Cut Line= 3
      1382685.74      6870009.19      1383638.43      6869671.09
      1383936.35      6868823.21
#Sta/Elev= 30
  3989.1 2070.41  4030.8 2067.95  4062.3 2068.29  4083.8 2067.06  4105.0 2064.11
  4257.6 2063.07  4344.5 2062.05  4418.1 2059.29  4450.6 2058.36  4623.5 2057.59
  4709.9 2057.75  4731.1 2060.70  4751.1 2060.43  4756.4 2058.08  4794.8 2054.79
  4934.7 2054.70  5005.5 2054.21  5006.0 2053.71  5022.2 2054.21  5088.1 2054.52
  5204.7 2054.72  5268.3 2059.75  5367.8 2060.84  5396.4 2065.33  5416.7 2065.77
  5437.9 2064.22  5554.4 2067.07  5754.7 2073.26  5878.6 2079.57  5898.7 2079.09
#Mann=11,-1,0
  3989.1   0.035       0  4257.6    0.07       0  4344.5   0.035       0
  4418.1    0.07       0  4450.6   0.035       0  4623.5    0.07       0
  4934.7   0.035       0  5005.5   0.035       0  5022.2   0.035       0
  5088.1    0.16       0  5396.4   0.035       0
Bank Sta=5005.5,5022.2
Exp/Cntr=0.3,0.1

Chan Stop Cuts=-1