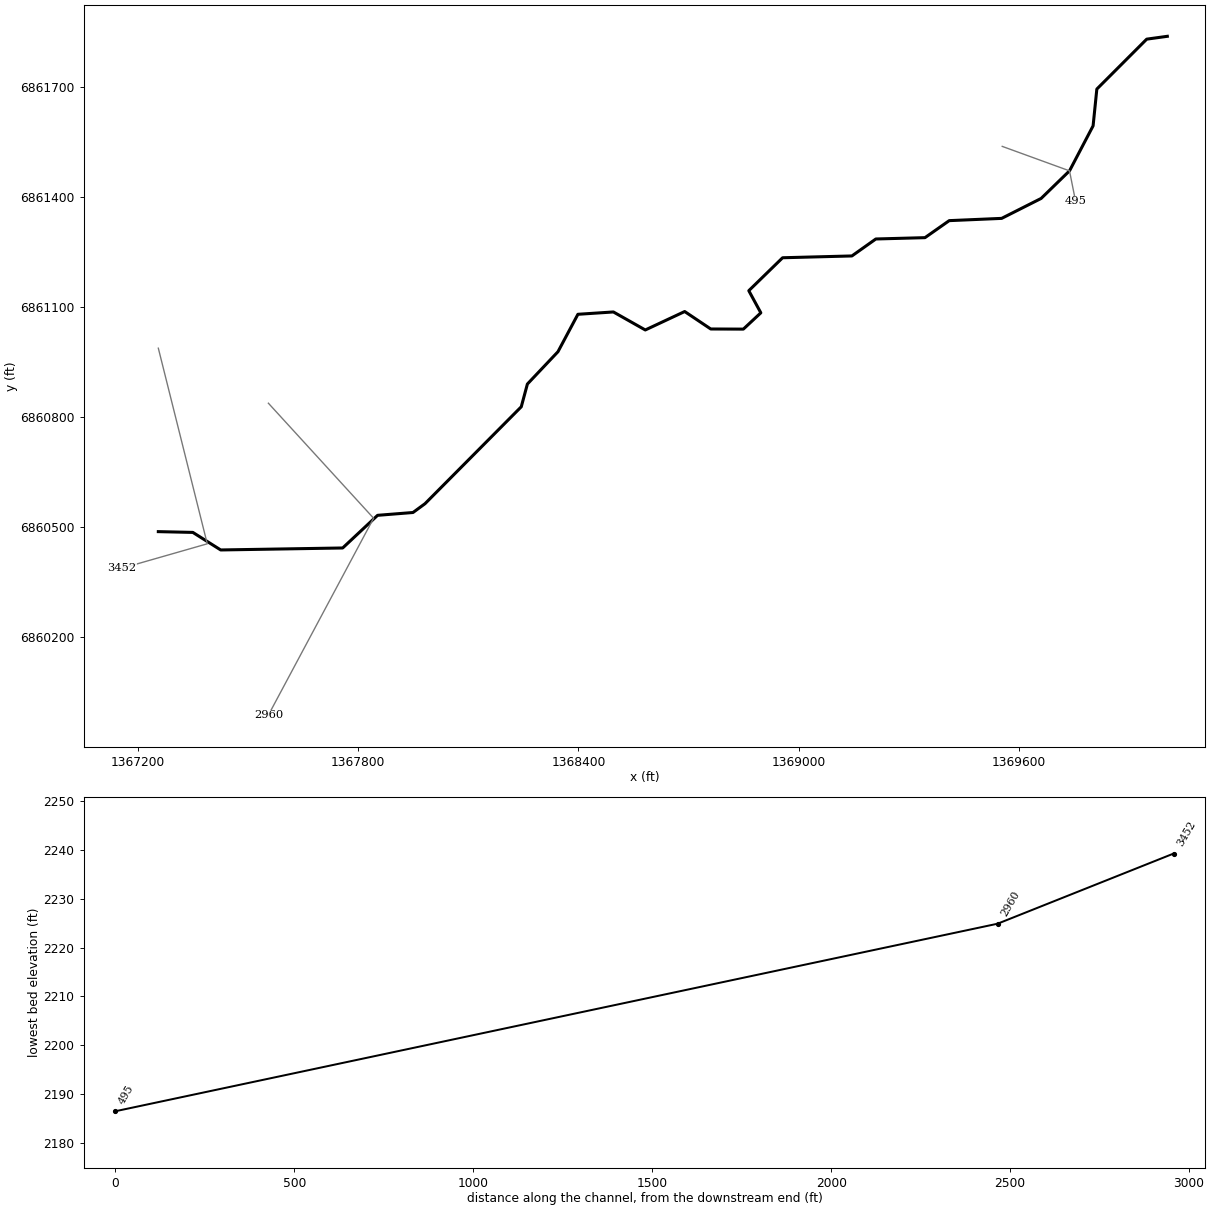
--- Sweetwater Creek Trib 27 T8_1.prj (project) ---

Proj Title=Sweetwater Creek Trib 27 T8_1 Base Level Engineering
Current Plan=p01
Default Exp/Contr=0.3,0.1
English Units
Geom File=g01
Flow File=f01
Plan File=p01
BEGIN DESCRIPTION:
Sweetwater Creek Trib 27 T8_1
END DESCRIPTION:

--- Sweetwater Creek Trib 27 T8_1.p01 (plan) ---

Plan Title=Multiple Run
Short Identifier=Multiple
Geom File=g01
Flow File=f01
Subcritical Flow
K Sum by GR= 0
Std Step Tol= 0.01
Critical Tol= 0.01
Num of Std Step Trials= 20
Max Error Tol= 0.3
Flow Tol Ratio= 0.001
Split Flow NTrial= 30
Split Flow Tol= 0.02
Split Flow Ratio= 0.02
Log Output Level= 0
Friction Slope Method= 1
Unsteady Friction Slope Method= 2
Unsteady Bridges Friction Slope Method= 1
Parabolic Critical Depth
Global Vel Dist=  1 , 1 , 1
Global Log Level= 0
CheckData=True
Encroach Param= -1, 0, 0, 0
BEGIN DESCRIPTION:
Multiple Run
END DESCRIPTION:

--- Sweetwater Creek Trib 27 T8_1.f01 (steady flow) ---

Flow Title=Multiple
Number of Profiles=7
Profile Names=10-year,25-year,50-year,1pct_min,100-year,1pct_plu,500-year
River Rch & RM= Sweetwater Creek,Reach-1,3452
     143     198     243     149     297     593     450
Boundary for River Rch & Prof#=Sweetwater Creek,Reach-1,1
Up Type=0
Dn Type=3
Dn Slope=0.005
Boundary for River Rch & Prof#=Sweetwater Creek,Reach-1,2
Up Type=0
Dn Type=3
Dn Slope=0.005
Boundary for River Rch & Prof#=Sweetwater Creek,Reach-1,3
Up Type=0
Dn Type=3
Dn Slope=0.005
Boundary for River Rch & Prof#=Sweetwater Creek,Reach-1,4
Up Type=0
Dn Type=3
Dn Slope=0.005
Boundary for River Rch & Prof#=Sweetwater Creek,Reach-1,5
Up Type=0
Dn Type=3
Dn Slope=0.005
Boundary for River Rch & Prof#=Sweetwater Creek,Reach-1,6
Up Type=0
Dn Type=3
Dn Slope=0.005
Boundary for River Rch & Prof#=Sweetwater Creek,Reach-1,7
Up Type=0
Dn Type=3
Dn Slope=0.005

--- Sweetwater Creek Trib 27 T8_1.g01 (geometry) ---

Geom Title=Existing Conditions

River Reach=Sweetwater Creek,Reach-1
Reach XY= 30
      1367255.00      6860488.00      1367349.13      6860485.90
      1367425.03      6860438.06      1367757.45      6860443.47
      1367852.58      6860532.46      1367949.11      6860540.15
      1367981.87      6860564.18      1368244.22      6860828.32
      1368260.87      6860890.28      1368344.19      6860978.35
      1368398.55      6861080.36      1368495.29      6861086.72
      1368582.20      6861037.63      1368689.60      6861087.90
      1368760.57      6861040.31      1368849.50      6861039.96
      1368897.11      6861084.38      1368864.30      6861144.68
      1368956.44      6861234.46      1369145.34      6861239.38
      1369210.53      6861285.61      1369344.49      6861289.23
      1369410.53      6861335.61      1369553.44      6861341.76
      1369661.07      6861396.13      1369738.37      6861471.29
      1369802.67      6861593.97      1369812.86      6861694.17
      1369948.79      6861830.24      1370005.00      6861838.00

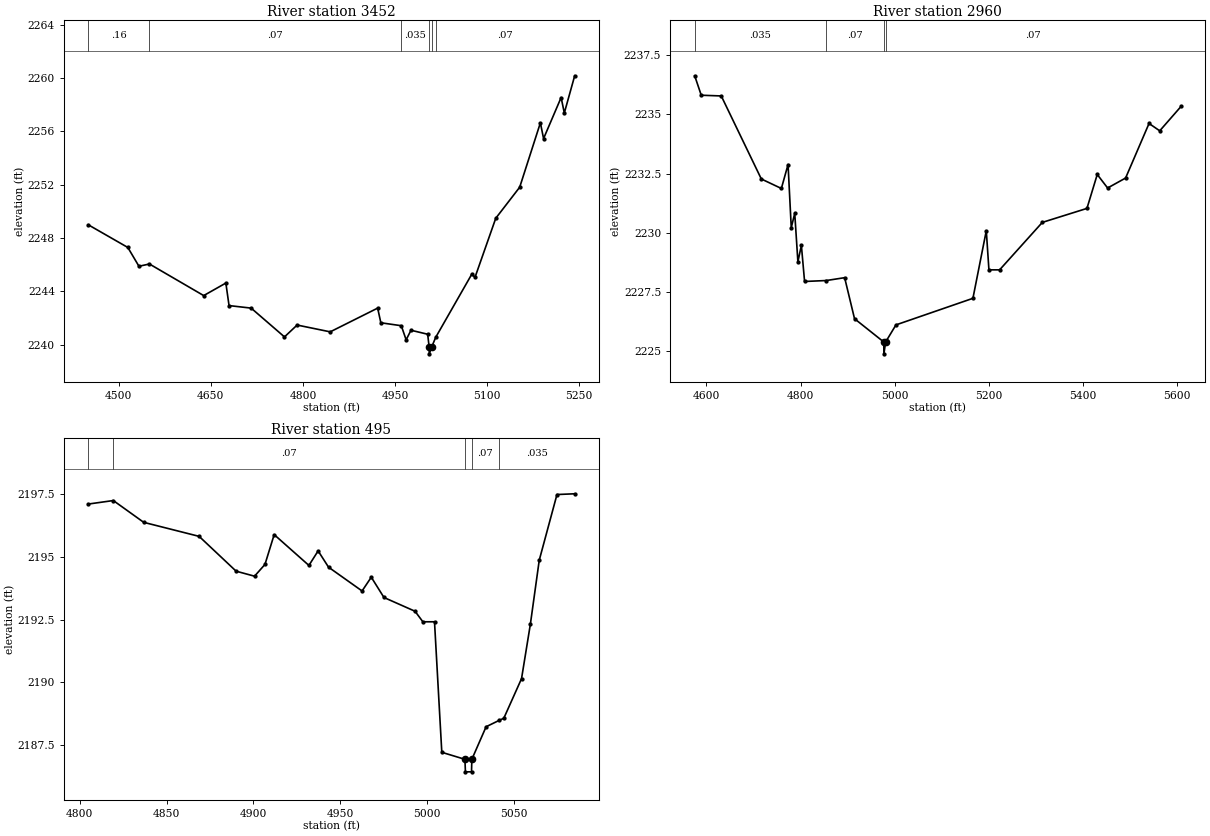
Type RM Length L Ch R = 1,3452,492,492,492
BEGIN DESCRIPTION:
Sweetwater Creek Trib 27 T8_1 2.0
END DESCRIPTION:
XS GIS Cut Line= 3
      1367255.00      6860987.99      1367388.40      6860454.83
      1367154.98      6860387.99
#Sta/Elev= 30
  4450.4 2248.98  4514.8 2247.28  4532.9 2245.87  4550.0 2246.04  4638.4 2243.67
  4674.5 2244.61  4679.7 2242.92  4715.7 2242.73  4770.0 2240.57  4790.6 2241.46
  4844.5 2240.95  4921.8 2242.73  4927.0 2241.63  4960.3 2241.41  4968.2 2240.35
  4976.1 2241.07  5003.3 2240.77  5005.7 2239.80  5005.9 2239.30  5009.7 2239.80
  5016.4 2240.54  5075.2 2245.28  5080.4 2245.04  5114.2 2249.47  5153.2 2251.80
  5186.9 2256.63  5192.1 2255.45  5220.7 2258.53  5225.9 2257.37  5242.8 2260.16
#Mann=6,-1,0
  4450.4    0.16       0  4550.0    0.07       0  4960.3   0.035       0
  5005.7   0.035       0  5009.7   0.035       0  5016.4    0.07       0
Bank Sta=5005.7,5009.7
Exp/Cntr=0.3,0.1

Type RM Length L Ch R = 1,2960,2465,2465,2465
BEGIN DESCRIPTION:
Sweetwater Creek Trib 27 T8_1 1.0
END DESCRIPTION:
XS GIS Cut Line= 3
      1367554.99      6860838.01      1367841.71      6860524.57
      1367554.98      6859987.97
#Sta/Elev= 30
  4575.2 2236.62  4589.1 2235.80  4631.6 2235.77  4716.7 2232.27  4759.3 2231.87
  4773.5 2232.88  4780.3 2230.22  4787.7 2230.82  4794.4 2228.78  4801.8 2229.47
  4808.6 2227.95  4854.7 2227.99  4893.7 2228.11  4914.7 2226.38  4976.8 2225.40
  4977.1 2224.90  4980.8 2225.40  5002.7 2226.12  5166.2 2227.24  5194.6 2230.09
  5200.2 2228.44  5222.9 2228.44  5313.6 2230.44  5408.4 2231.03  5430.3 2232.46
  5452.3 2231.89  5490.5 2232.31  5540.3 2234.61  5563.0 2234.30  5608.4 2235.33
#Mann=4,-1,0
  4575.2   0.035       0  4854.7    0.07       0  4976.8    0.07       0
  4980.8    0.07       0
Bank Sta=4976.8,4980.8
Exp/Cntr=0.3,0.1

Type RM Length L Ch R = 1,495,0,0,0
BEGIN DESCRIPTION:
Sweetwater Creek Trib 27 T8_1 2787
END DESCRIPTION:
XS GIS Cut Line= 3
      1369555.03      6861537.99      1369738.37      6861471.29
      1369754.99      6861388.03
#Sta/Elev= 30
  4804.9 2197.11  4819.3 2197.25  4836.8 2196.38  4868.7 2195.82  4890.0 2194.43
  4900.6 2194.23  4906.6 2194.70  4911.9 2195.89  4931.9 2194.66  4937.2 2195.24
  4943.2 2194.59  4962.5 2193.64  4967.8 2194.19  4975.1 2193.38  4993.0 2192.83
  4997.5 2192.41  5004.2 2192.41  5008.4 2187.20  5021.7 2186.92  5022.0 2186.42
  5025.5 2186.42  5025.7 2186.92  5033.9 2188.22  5041.3 2188.47  5044.1 2188.56
  5054.3 2190.14  5059.4 2192.32  5064.5 2194.87  5074.7 2197.49  5084.9 2197.52
#Mann=5,-1,0
  4804.9   0.045       0  4819.3    0.07       0  5021.7    0.07       0
  5025.7    0.07       0  5041.3   0.035       0
Bank Sta=5021.7,5025.7
Exp/Cntr=0.3,0.1

Chan Stop Cuts=-1