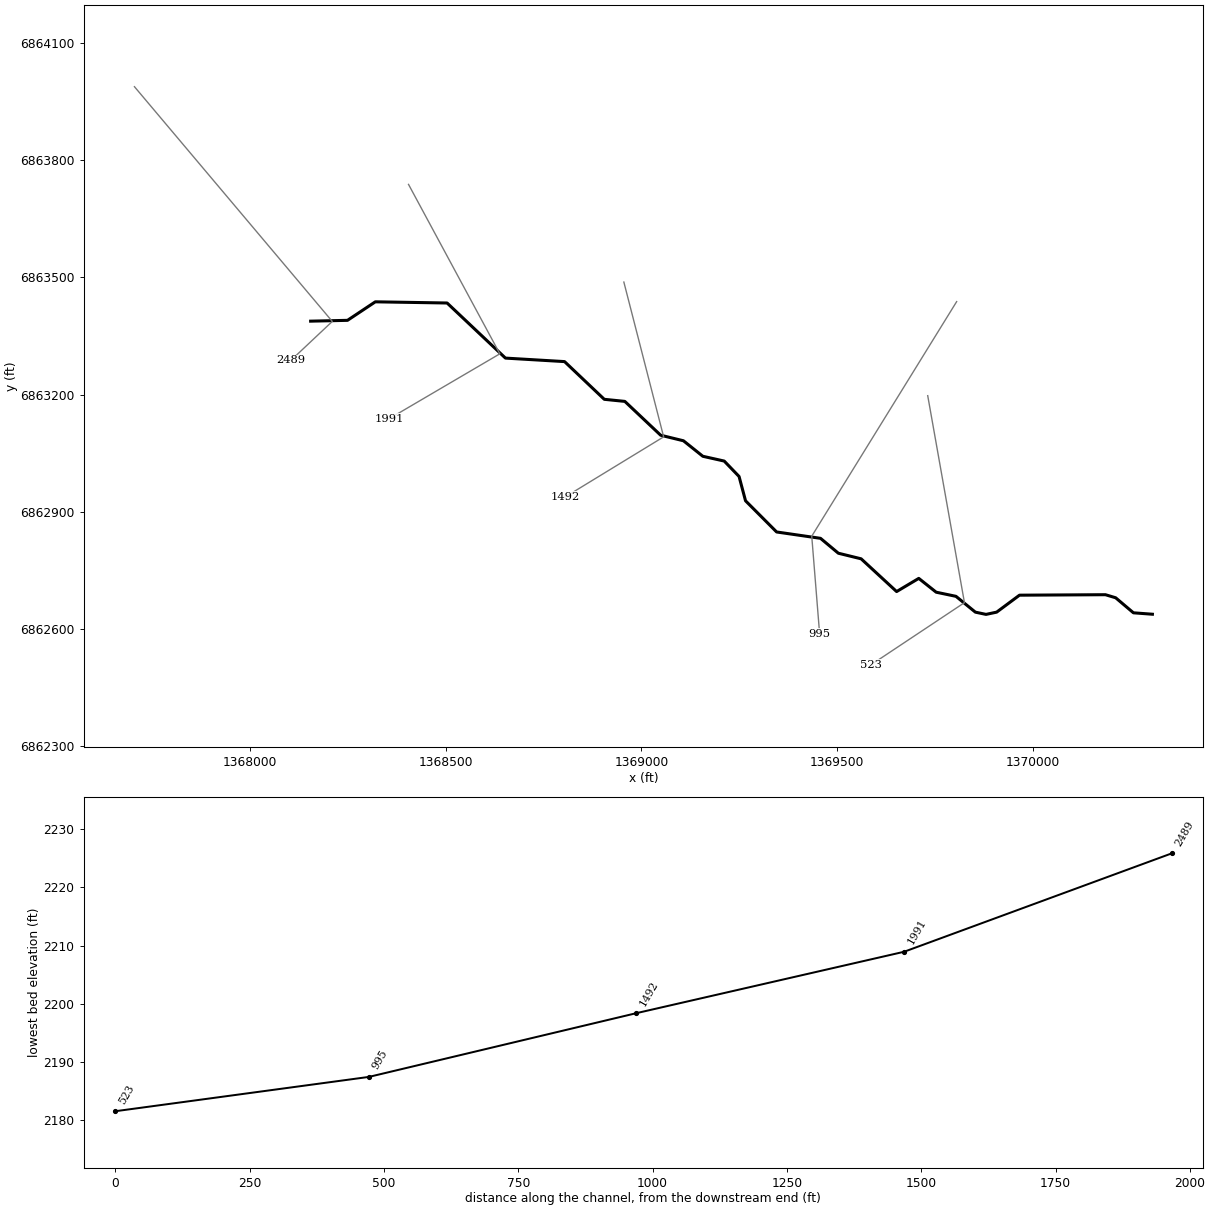
--- Sweetwater Creek Trib 27 T8_2.prj (project) ---

Proj Title=Sweetwater Creek Trib 27 T8_2 Base Level Engineering
Current Plan=p01
Default Exp/Contr=0.3,0.1
English Units
Geom File=g01
Flow File=f01
Plan File=p01
Y Axis Title=Elevation
X Axis Title(PF)=Main Channel Distance
X Axis Title(XS)=Station
BEGIN DESCRIPTION:
Sweetwater Creek Trib 27 T8_2
END DESCRIPTION:
DSS Export Rating Curves= 0
DSS Export Rating Curve Sorted= 0
DSS Export Volume Flow Curves= 0
DXF OffsetX= 0
DXF OffsetY= 0
DXF ScaleX= 1
DXF ScaleY= 10

--- Sweetwater Creek Trib 27 T8_2.p01 (plan) ---

Plan Title=Multiple Run
Short Identifier=Multiple
Geom File=g01
Flow File=f01
Subcritical Flow
K Sum by GR= 0
Std Step Tol= 0.01
Critical Tol= 0.01
Num of Std Step Trials= 20
Max Error Tol= 0.3
Flow Tol Ratio= 0.001
Split Flow NTrial= 30
Split Flow Tol= 0.02
Split Flow Ratio= 0.02
Log Output Level= 0
Friction Slope Method= 1
Unsteady Friction Slope Method= 2
Unsteady Bridges Friction Slope Method= 1
Parabolic Critical Depth
Global Vel Dist=  1 , 1 , 1
Global Log Level= 0
CheckData=True
Encroach Param= -1, 0, 0, 0
BEGIN DESCRIPTION:
Multiple Run
END DESCRIPTION:

--- Sweetwater Creek Trib 27 T8_2.f01 (steady flow) ---

Flow Title=Multiple
Number of Profiles=7
Profile Names=10-year,25-year,50-year,1pct_min,100-year,1pct_plu,500-year
River Rch & RM= Sweetwater Creek,Reach-1,2489
      68      88     104      61     122     244     170
Boundary for River Rch & Prof#=Sweetwater Creek,Reach-1,1
Up Type=0
Dn Type=3
Dn Slope=0.005
Boundary for River Rch & Prof#=Sweetwater Creek,Reach-1,2
Up Type=0
Dn Type=3
Dn Slope=0.005
Boundary for River Rch & Prof#=Sweetwater Creek,Reach-1,3
Up Type=0
Dn Type=3
Dn Slope=0.005
Boundary for River Rch & Prof#=Sweetwater Creek,Reach-1,4
Up Type=0
Dn Type=3
Dn Slope=0.005
Boundary for River Rch & Prof#=Sweetwater Creek,Reach-1,5
Up Type=0
Dn Type=3
Dn Slope=0.005
Boundary for River Rch & Prof#=Sweetwater Creek,Reach-1,6
Up Type=0
Dn Type=3
Dn Slope=0.005
Boundary for River Rch & Prof#=Sweetwater Creek,Reach-1,7
Up Type=0
Dn Type=3
Dn Slope=0.005

--- Sweetwater Creek Trib 27 T8_2.g01 (geometry) ---

Geom Title=Existing Conditions

River Reach=Sweetwater Creek,Reach-1
Reach XY= 30
      1368155.00      6863388.00      1368249.13      6863390.10
      1368320.21      6863437.49      1368503.54      6863434.46
      1368652.55      6863293.47      1368803.55      6863284.51
      1368905.00      6863188.00      1368957.51      6863182.67
      1369048.95      6863096.14      1369107.19      6863081.90
      1369156.76      6863042.20      1369211.34      6863029.98
      1369249.25      6862990.54      1369265.78      6862928.31
      1369345.19      6862848.51      1369457.32      6862832.23
      1369502.83      6862794.14      1369561.06      6862779.82
      1369651.67      6862696.01      1369708.23      6862729.75
      1369752.70      6862694.37      1369803.26      6862683.81
      1369852.80      6862643.34      1369880.00      6862637.59
      1369907.18      6862643.37      1369965.50      6862686.76
      1370184.99      6862687.98      1370211.16      6862680.11
      1370256.51      6862641.65      1370305.00      6862638.00

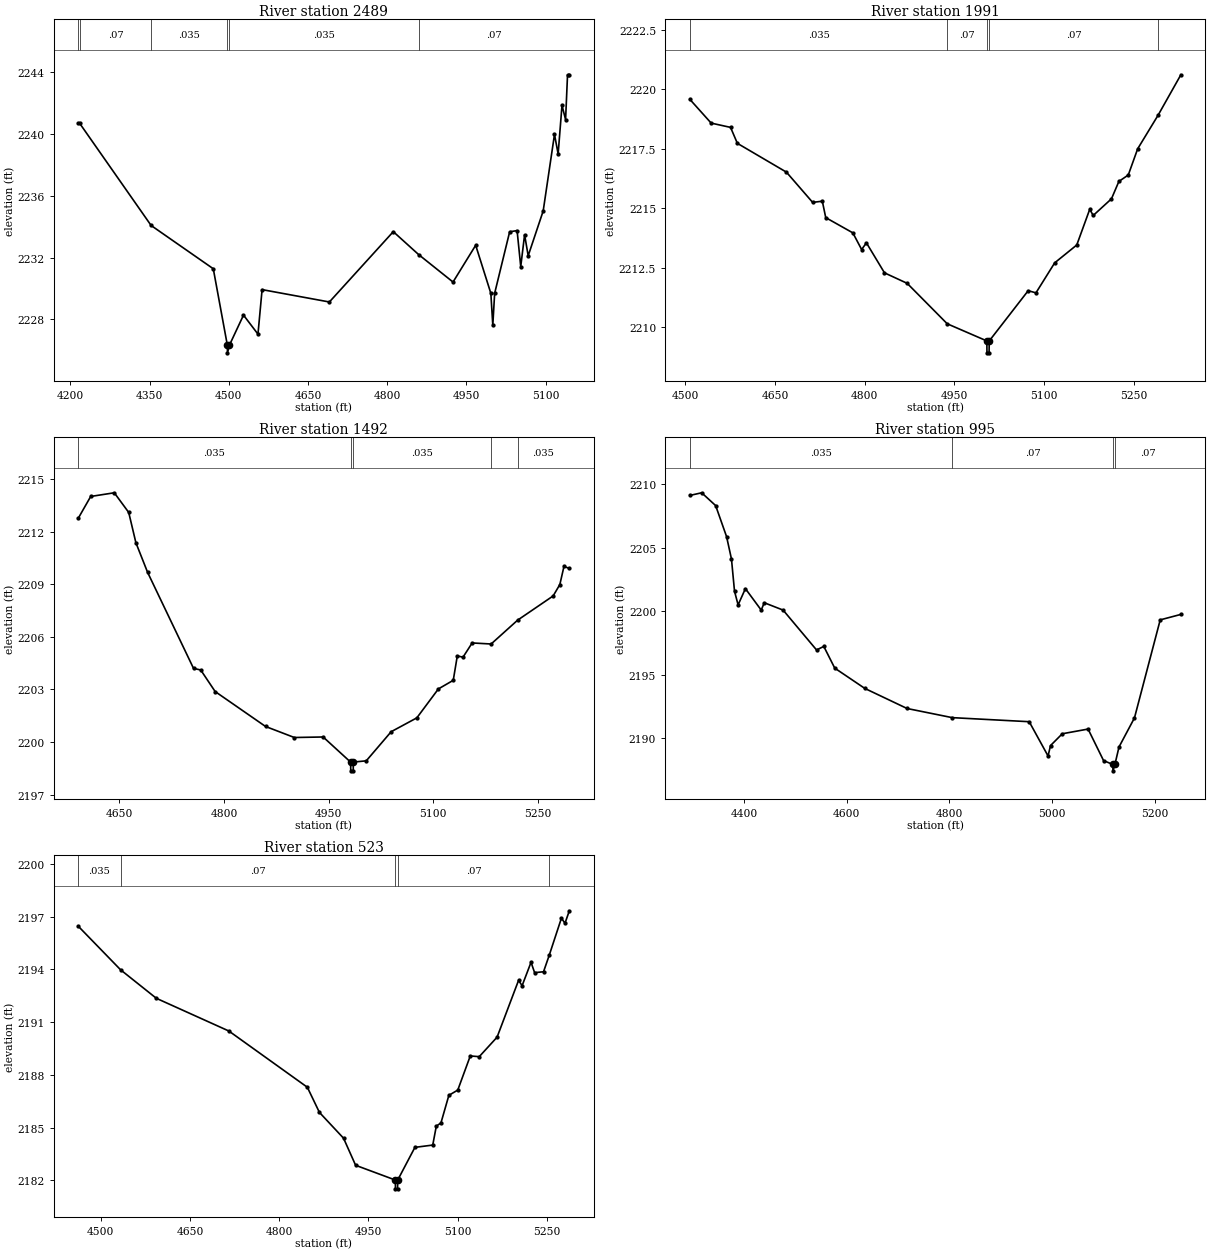
Type RM Length L Ch R = 1,2489,498,498,498
BEGIN DESCRIPTION:
Sweetwater Creek Trib 27 T8_2 4.0
END DESCRIPTION:
XS GIS Cut Line= 3
      1367704.97      6863988.03      1368210.29      6863387.30
      1368105.02      6863288.02
#Sta/Elev= 30
  4215.0 2240.68  4217.8 2240.68  4352.9 2234.08  4470.6 2231.28  4497.2 2226.34
  4497.5 2225.84  4501.2 2226.34  4527.8 2228.28  4555.2 2227.05  4563.0 2229.93
  4690.4 2229.13  4811.4 2233.68  4859.3 2232.20  4924.5 2230.42  4967.4 2232.80
  4996.1 2229.69  4999.8 2227.63  5003.3 2229.69  5031.7 2233.67  5045.8 2233.75
  5052.7 2231.42  5060.0 2233.48  5066.8 2232.12  5095.2 2235.02  5116.6 2239.97
  5123.5 2238.71  5130.8 2241.85  5137.6 2240.93  5141.3 2243.83  5144.7 2243.83
#Mann=6,-1,0
  4215.0   0.035       0  4217.8    0.07       0  4352.9   0.035       0
  4497.2    0.07       0  4501.2   0.035       0  4859.3    0.07       0
Bank Sta=4497.2,4501.2
Exp/Cntr=0.3,0.1

Type RM Length L Ch R = 1,1991,499,499,499
BEGIN DESCRIPTION:
Sweetwater Creek Trib 27 T8_2 3.0
END DESCRIPTION:
XS GIS Cut Line= 3
      1368405.01      6863737.98      1368638.24      6863304.43
      1368355.01      6863138.01
#Sta/Elev= 30
  4507.7 2219.58  4543.4 2218.58  4575.8 2218.40  4587.2 2217.73  4669.2 2216.52
  4713.0 2215.25  4729.2 2215.30  4734.9 2214.61  4780.2 2213.97  4794.9 2213.27
  4802.9 2213.55  4833.1 2212.29  4871.0 2211.85  4938.0 2210.15  5004.2 2209.43
  5004.4 2208.93  5007.9 2208.93  5008.2 2209.43  5073.3 2211.54  5086.3 2211.45
  5117.6 2212.71  5154.5 2213.46  5176.2 2214.96  5182.0 2214.70  5212.5 2215.40
  5224.9 2216.13  5240.6 2216.40  5256.3 2217.50  5290.4 2218.91  5328.5 2220.61
#Mann=5,-1,0
  4507.7   0.035       0  4938.0    0.07       0  5004.2    0.07       0
  5008.2    0.07       0  5290.4   0.035       0
Bank Sta=5004.2,5008.2
Exp/Cntr=0.3,0.1

Type RM Length L Ch R = 1,1492,497,497,497
BEGIN DESCRIPTION:
Sweetwater Creek Trib 27 T8_2 2.0
END DESCRIPTION:
XS GIS Cut Line= 3
      1368955.00      6863488.02      1369056.64      6863091.95
      1368804.99      6862938.00
#Sta/Elev= 30
  4591.1 2212.76  4608.9 2214.00  4642.7 2214.21  4663.4 2213.09  4673.7 2211.36
  4690.4 2209.68  4756.3 2204.20  4766.6 2204.11  4787.3 2202.88  4859.5 2200.89
  4900.8 2200.26  4942.1 2200.29  4981.4 2198.86  4981.7 2198.36  4985.2 2198.36
  4985.4 2198.86  5003.9 2198.93  5039.6 2200.59  5076.4 2201.38  5107.3 2203.03
  5128.6 2203.52  5134.4 2204.91  5142.6 2204.84  5155.7 2205.65  5182.9 2205.59
  5220.9 2206.95  5271.8 2208.33  5281.4 2208.98  5287.3 2210.01  5295.0 2209.90
#Mann=5,-1,0
  4591.1   0.035       0  4981.4   0.035       0  4985.4   0.035       0
  5182.9    0.07       0  5220.9   0.035       0
Bank Sta=4981.4,4985.4
Exp/Cntr=0.3,0.1

Type RM Length L Ch R = 1,995,472,472,472
BEGIN DESCRIPTION:
Sweetwater Creek Trib 27 T8_2 1.0
END DESCRIPTION:
XS GIS Cut Line= 3
      1369805.02      6863438.03      1369434.90      6862837.76
      1369455.00      6862587.97
#Sta/Elev= 30
  4294.8 2209.11  4317.9 2209.32  4345.1 2208.31  4366.4 2205.86  4375.9 2204.10
  4381.8 2201.57  4388.8 2200.49  4403.0 2201.77  4433.8 2200.08  4439.7 2200.66
  4476.4 2200.08  4541.5 2196.94  4555.6 2197.22  4576.9 2195.51  4635.5 2193.91
  4717.7 2192.33  4805.6 2191.61  4955.4 2191.29  4992.1 2188.59  4996.9 2189.41
  5019.8 2190.34  5070.0 2190.71  5100.1 2188.23  5118.2 2187.92  5118.4 2187.42
  5122.2 2187.92  5130.2 2189.30  5160.3 2191.59  5210.4 2199.31  5250.6 2199.74
#Mann=4,-1,0
  4294.8   0.035       0  4805.6    0.07       0  5118.2    0.07       0
  5122.2    0.07       0
Bank Sta=5118.2,5122.2
Exp/Cntr=0.3,0.1

Type RM Length L Ch R = 1,523,0,0,0
BEGIN DESCRIPTION:
Sweetwater Creek Trib 27 T8_2 2755
END DESCRIPTION:
XS GIS Cut Line= 3
      1369731.11      6863197.28      1369824.93      6862667.63
      1369585.32      6862508.02
#Sta/Elev= 30
  4462.1 2196.46  4533.3 2193.98  4593.4 2192.36  4715.3 2190.50  4847.3 2187.30
  4867.6 2185.87  4908.2 2184.40  4928.5 2182.86  4995.3 2182.02  4995.5 2181.52
  4999.0 2181.52  4999.3 2182.02  5028.2 2183.88  5058.2 2184.01  5064.2 2185.09
  5072.0 2185.27  5085.3 2186.84  5100.3 2187.14  5121.3 2189.08  5136.4 2189.04
  5166.4 2190.15  5202.5 2193.38  5208.5 2193.08  5223.5 2194.41  5229.5 2193.82
  5244.5 2193.87  5254.0 2194.80  5274.6 2196.92  5280.6 2196.63  5287.9 2197.34
#Mann=5,-1,0
  4462.1   0.035       0  4533.3    0.07       0  4995.3    0.07       0
  4999.3    0.07       0  5254.0   0.035       0
Bank Sta=4995.3,4999.3
Exp/Cntr=0.3,0.1

Chan Stop Cuts=-1