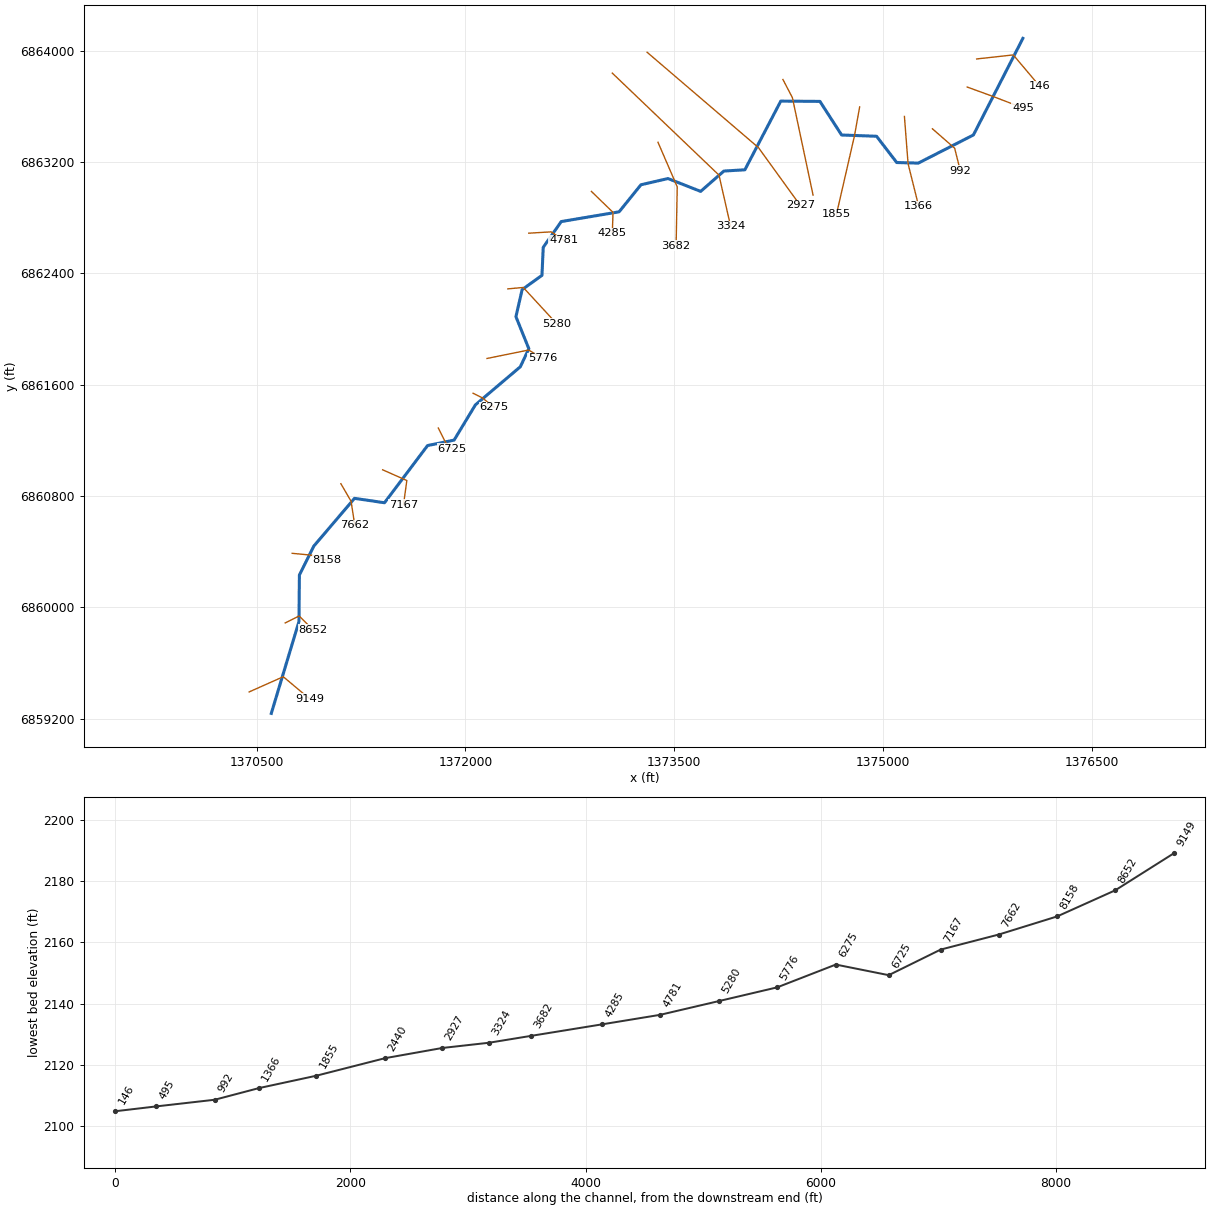
--- Sweetwater Creek Trib 27 T8_3.prj (project) ---

Proj Title=Sweetwater Creek Trib 27 T8_3 Base Level Engineering
Current Plan=p01
Default Exp/Contr=0.3,0.1
English Units
Geom File=g01
Flow File=f01
Plan File=p01
BEGIN DESCRIPTION:
Sweetwater Creek Trib 27 T8_3
END DESCRIPTION:

--- Sweetwater Creek Trib 27 T8_3.p01 (plan) ---

Plan Title=Multiple Run
Short Identifier=Multiple
Geom File=g01
Flow File=f01
Subcritical Flow
K Sum by GR= 0
Std Step Tol= 0.01
Critical Tol= 0.01
Num of Std Step Trials= 20
Max Error Tol= 0.3
Flow Tol Ratio= 0.001
Split Flow NTrial= 30
Split Flow Tol= 0.02
Split Flow Ratio= 0.02
Log Output Level= 0
Friction Slope Method= 1
Unsteady Friction Slope Method= 2
Unsteady Bridges Friction Slope Method= 1
Parabolic Critical Depth
Global Vel Dist=  1 , 1 , 1
Global Log Level= 0
CheckData=True
Encroach Param= -1, 0, 0, 0
BEGIN DESCRIPTION:
Multiple Run
END DESCRIPTION:

--- Sweetwater Creek Trib 27 T8_3.f01 (steady flow) ---

Flow Title=Multiple
Number of Profiles=7
Profile Names=10-year,25-year,50-year,1pct_min,100-year,1pct_plu,500-year
River Rch & RM= Sweetwater Creek,Reach-1,9149
     139     190     232     142     282     563     423
River Rch & RM= Sweetwater Creek,Reach-1,6725
     266     378     472     293     586    1168     912
River Rch & RM= Sweetwater Creek,Reach-1,3682
     292     415     519     322     643    1282    1000
Boundary for River Rch & Prof#=Sweetwater Creek,Reach-1,1
Up Type=0
Dn Type=3
Dn Slope=0.005
Boundary for River Rch & Prof#=Sweetwater Creek,Reach-1,2
Up Type=0
Dn Type=3
Dn Slope=0.005
Boundary for River Rch & Prof#=Sweetwater Creek,Reach-1,3
Up Type=0
Dn Type=3
Dn Slope=0.005
Boundary for River Rch & Prof#=Sweetwater Creek,Reach-1,4
Up Type=0
Dn Type=3
Dn Slope=0.005
Boundary for River Rch & Prof#=Sweetwater Creek,Reach-1,5
Up Type=0
Dn Type=3
Dn Slope=0.005
Boundary for River Rch & Prof#=Sweetwater Creek,Reach-1,6
Up Type=0
Dn Type=3
Dn Slope=0.005
Boundary for River Rch & Prof#=Sweetwater Creek,Reach-1,7
Up Type=0
Dn Type=3
Dn Slope=0.005

--- Sweetwater Creek Trib 27 T8_3.g01 (geometry) ---

Geom Title=Existing Conditions

River Reach=Sweetwater Creek,Reach-1
Reach XY= 30
      1370605.00      6859238.00      1370803.80      6859898.50
      1370806.84      6860231.88      1370910.83      6860440.30
      1371202.70      6860782.91      1371418.30      6860751.34
      1371727.76      6861162.15      1371918.32      6861201.37
      1372071.46      6861454.75      1372394.25      6861728.30
      1372455.30      6861858.17      1372362.56      6862088.00
      1372406.99      6862282.32      1372549.64      6862385.30
      1372558.75      6862586.45      1372688.21      6862771.56
      1373103.75      6862841.45      1373260.85      6863035.94
      1373455.10      6863080.67      1373689.84      6862988.36
      1373856.47      6863134.46      1374007.46      6863143.46
      1374265.43      6863636.96      1374546.72      6863634.94
      1374702.53      6863393.45      1374953.55      6863384.47
      1375098.53      6863195.69      1375253.53      6863191.54
      1375649.41      6863393.61      1376005.00      6864088.00

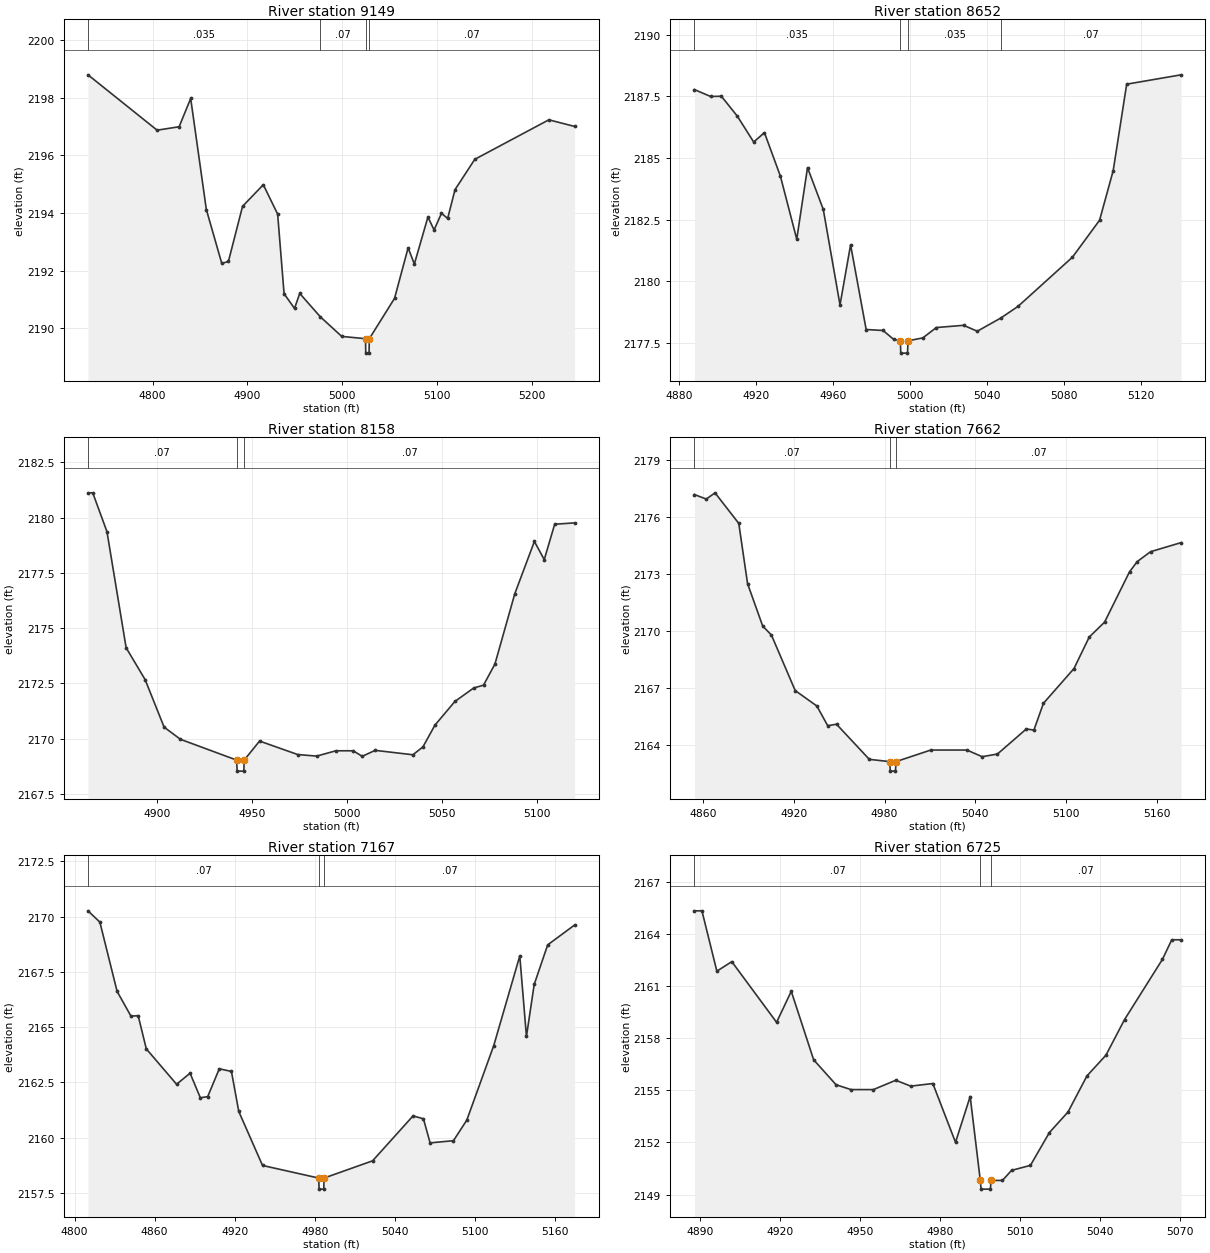
Type RM Length L Ch R = 1,9149,497,497,497
BEGIN DESCRIPTION:
Sweetwater Creek Trib 27 T8_3 16.0
END DESCRIPTION:
XS GIS Cut Line= 3
      1370446.07      6859392.19      1370690.99      6859501.23
      1370878.97      6859343.95
#Sta/Elev= 30
  4731.9 2198.79  4804.8 2196.87  4828.0 2196.99  4840.2 2197.97  4856.7 2194.12
  4873.0 2192.25  4880.0 2192.32  4894.9 2194.23  4916.8 2194.98  4931.9 2193.96
  4938.7 2191.20  4949.7 2190.69  4955.2 2191.21  4976.9 2190.40  4999.5 2189.72
  5024.6 2189.64  5024.8 2189.14  5028.3 2189.14  5028.6 2189.64  5055.2 2191.04
  5069.5 2192.79  5076.1 2192.23  5090.4 2193.86  5096.9 2193.41  5104.7 2193.99
  5111.2 2193.81  5119.0 2194.81  5139.8 2195.86  5217.9 2197.23  5245.1 2197.00
#Mann=4,-1,0
  4731.9   0.035       0  4976.9    0.07       0  5024.6    0.07       0
  5028.6    0.07       0
Bank Sta=5024.6,5028.6
Exp/Cntr=0.3,0.1

Type RM Length L Ch R = 1,8652,494,494,494
BEGIN DESCRIPTION:
Sweetwater Creek Trib 27 T8_3 15.0
END DESCRIPTION:
XS GIS Cut Line= 3
      1370704.99      6859888.00      1370805.40      6859937.83
      1370904.99      6859838.01
#Sta/Elev= 30
  4887.9 2187.78  4896.3 2187.50  4901.9 2187.51  4910.2 2186.70  4918.7 2185.65
  4924.3 2186.03  4932.6 2184.26  4941.1 2181.70  4946.7 2184.61  4954.9 2182.91
  4963.6 2179.03  4969.1 2181.47  4977.2 2178.03  4986.0 2177.99  4991.5 2177.63
  4995.0 2177.57  4995.2 2177.07  4998.7 2177.07  4999.0 2177.57  5006.7 2177.69
  5013.7 2178.11  5027.9 2178.20  5035.0 2177.96  5047.3 2178.50  5056.2 2178.97
  5084.5 2180.97  5098.6 2182.47  5105.7 2184.49  5112.7 2188.00  5141.0 2188.38
#Mann=4,-1,0
  4887.9   0.035       0  4995.0   0.035       0  4999.0   0.035       0
  5047.3    0.07       0
Bank Sta=4995,4999
Exp/Cntr=0.3,0.1

Type RM Length L Ch R = 1,8158,496,496,496
BEGIN DESCRIPTION:
Sweetwater Creek Trib 27 T8_3 14.0
END DESCRIPTION:
XS GIS Cut Line= 3
      1370755.04      6860388.00      1370891.02      6860374.94
      1371004.98      6860338.01
#Sta/Elev= 30
  4863.4 2181.12  4865.9 2181.12  4873.4 2179.36  4883.5 2174.11  4893.5 2172.67
  4903.5 2170.52  4912.1 2169.97  4941.7 2169.03  4942.0 2168.53  4945.5 2168.53
  4945.7 2169.03  4953.8 2169.89  4973.9 2169.28  4983.9 2169.21  4994.0 2169.45
  5003.1 2169.45  5007.9 2169.20  5014.7 2169.47  5034.6 2169.27  5039.9 2169.63
  5046.2 2170.61  5056.7 2171.68  5066.6 2172.29  5071.8 2172.42  5077.8 2173.37
  5088.3 2176.56  5098.6 2178.92  5103.8 2178.10  5109.3 2179.70  5119.8 2179.76
#Mann=3,-1,0
  4863.4    0.07       0  4941.7    0.07       0  4945.7    0.07       0
Bank Sta=4941.7,4945.7
Exp/Cntr=0.3,0.1

Type RM Length L Ch R = 1,7662,495,495,495
BEGIN DESCRIPTION:
Sweetwater Creek Trib 27 T8_3 13.0
END DESCRIPTION:
XS GIS Cut Line= 3
      1371105.02      6860887.96      1371178.18      6860761.96
      1371205.00      6860588.02
#Sta/Elev= 30
  4854.3 2177.17  4862.1 2176.93  4867.9 2177.26  4883.6 2175.65  4889.4 2172.48
  4899.4 2170.25  4905.2 2169.77  4920.9 2166.85  4935.2 2166.04  4942.4 2165.00
  4948.2 2165.08  4969.9 2163.23  4983.5 2163.11  4983.7 2162.61  4987.2 2162.61
  4987.5 2163.11  5010.5 2163.72  5034.4 2163.72  5044.5 2163.37  5054.6 2163.51
  5073.7 2164.83  5078.7 2164.77  5085.0 2166.18  5105.2 2168.01  5115.3 2169.67
  5125.4 2170.45  5141.9 2173.10  5147.0 2173.64  5155.8 2174.16  5176.0 2174.64
#Mann=3,-1,0
  4854.3    0.07       0  4983.5    0.07       0  4987.5    0.07       0
Bank Sta=4983.5,4987.5
Exp/Cntr=0.3,0.1

Type RM Length L Ch R = 1,7167,442,442,442
BEGIN DESCRIPTION:
Sweetwater Creek Trib 27 T8_3 12.0
END DESCRIPTION:
XS GIS Cut Line= 3
      1371405.03      6860987.99      1371578.70      6860911.18
      1371555.00      6860737.99
#Sta/Elev= 30
  4810.1 2170.26  4819.0 2169.75  4831.9 2166.62  4842.3 2165.50  4847.7 2165.52
  4853.8 2164.02  4876.5 2162.42  4886.6 2162.92  4894.3 2161.81  4899.8 2161.86
  4908.5 2163.12  4917.6 2163.00  4923.1 2161.19  4940.9 2158.75  4983.0 2158.18
  4983.3 2157.68  4986.8 2157.68  4987.0 2158.18  5023.4 2158.96  5053.7 2160.99
  5061.5 2160.86  5066.5 2159.77  5084.0 2159.87  5094.0 2160.80  5114.2 2164.17
  5133.7 2168.22  5138.7 2164.58  5144.5 2166.93  5154.6 2168.72  5174.8 2169.62
#Mann=3,-1,0
  4810.1    0.07       0  4983.0    0.07       0  4987.0    0.07       0
Bank Sta=4983,4987
Exp/Cntr=0.3,0.1

Type RM Length L Ch R = 1,6725,450,450,450
BEGIN DESCRIPTION:
Sweetwater Creek Trib 27 T8_3 11.0
END DESCRIPTION:
XS GIS Cut Line= 3
      1371805.00      6861288.00      1371855.15      6861187.64
      1371904.97      6861138.03
#Sta/Elev= 30
  4887.8 2165.36  4890.6 2165.36  4896.2 2161.88  4901.8 2162.43  4918.6 2158.93
  4924.1 2160.72  4932.5 2156.77  4940.9 2155.33  4946.5 2155.05  4954.9 2155.05
  4963.3 2155.59  4968.9 2155.25  4977.2 2155.40  4985.7 2152.01  4991.2 2154.65
  4995.0 2149.81  4995.3 2149.31  4998.8 2149.31  4999.0 2149.81  5003.3 2149.81
  5006.7 2150.39  5013.8 2150.68  5020.9 2152.57  5027.9 2153.76  5035.0 2155.84
  5042.1 2157.03  5049.1 2159.09  5063.3 2162.56  5066.8 2163.69  5070.3 2163.69
#Mann=3,-1,0
  4887.8    0.07       0  4995.0    0.07       0  4999.0    0.07       0
Bank Sta=4995,4999
Exp/Cntr=0.3,0.1

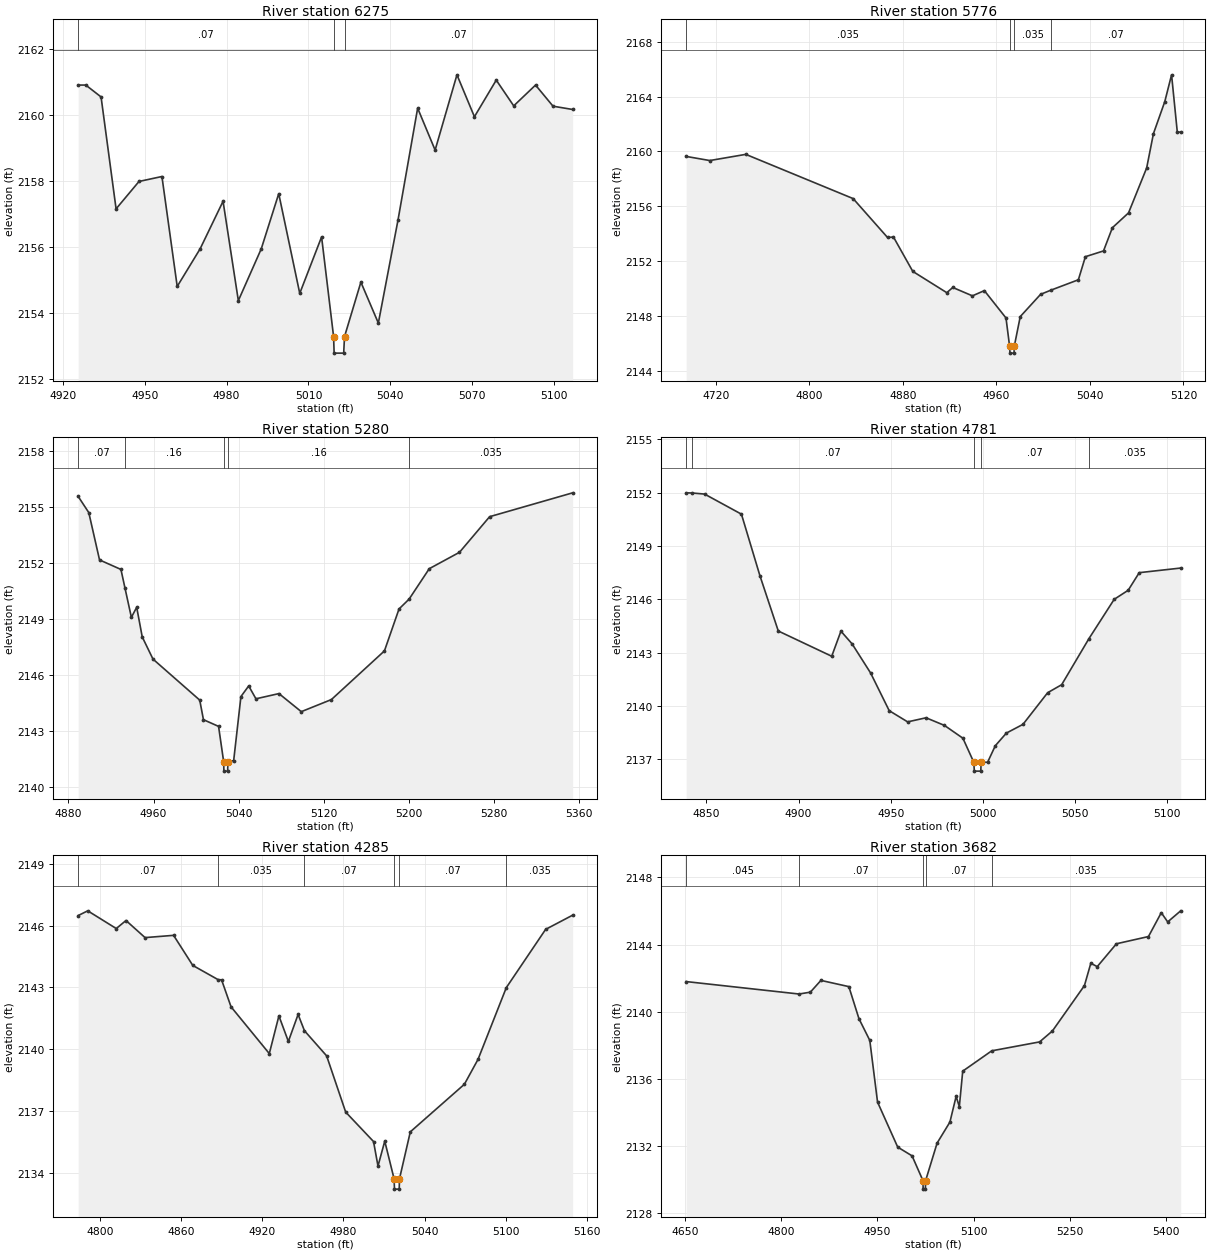
Type RM Length L Ch R = 1,6275,499,499,499
BEGIN DESCRIPTION:
Sweetwater Creek Trib 27 T8_3 10.0
END DESCRIPTION:
XS GIS Cut Line= 3
      1372055.02      6861537.99      1372121.57      6861504.71
      1372204.98      6861438.01
#Sta/Elev= 30
  4925.6 2160.90  4928.4 2160.90  4934.0 2160.54  4939.5 2157.15  4947.9 2157.98
  4956.3 2158.13  4961.9 2154.80  4970.3 2155.94  4978.7 2157.38  4984.3 2154.37
  4992.7 2155.94  4999.1 2157.61  5006.8 2154.59  5014.8 2156.30  5019.2 2153.28
  5019.4 2152.78  5022.9 2152.78  5023.2 2153.28  5029.2 2154.93  5035.6 2153.69
  5042.8 2156.81  5050.0 2160.20  5056.4 2158.93  5064.4 2161.21  5070.8 2159.94
  5078.8 2161.05  5085.2 2160.27  5093.2 2160.90  5099.6 2160.26  5106.8 2160.16
#Mann=3,-1,0
  4925.6    0.07       0  5019.2    0.07       0  5023.2    0.07       0
Bank Sta=5019.2,5023.2
Exp/Cntr=0.3,0.1

Type RM Length L Ch R = 1,5776,496,496,496
BEGIN DESCRIPTION:
Sweetwater Creek Trib 27 T8_3 9.0
END DESCRIPTION:
XS GIS Cut Line= 3
      1372155.04      6861788.01      1372454.25      6861848.68
      1372554.99      6861788.01
#Sta/Elev= 30
  4694.7 2159.64  4714.9 2159.34  4745.7 2159.79  4837.5 2156.57  4866.9 2153.74
  4872.0 2153.77  4888.5 2151.27  4917.6 2149.72  4922.7 2150.10  4939.5 2149.49
  4949.7 2149.87  4968.2 2147.88  4971.3 2145.82  4971.6 2145.32  4975.1 2145.32
  4975.3 2145.82  4980.4 2147.98  4997.8 2149.60  5006.5 2149.90  5030.1 2150.66
  5036.1 2152.34  5051.6 2152.76  5059.2 2154.45  5073.0 2155.53  5088.5 2158.80
  5094.3 2161.30  5104.0 2163.63  5109.8 2165.58  5114.7 2161.41  5117.6 2161.41
#Mann=4,-1,0
  4694.7   0.035       0  4971.3   0.035       0  4975.3   0.035       0
  5006.5    0.07       0
Bank Sta=4971.3,4975.3
Exp/Cntr=0.3,0.1

Type RM Length L Ch R = 1,5280,499,499,499
BEGIN DESCRIPTION:
Sweetwater Creek Trib 27 T8_3 8.0
END DESCRIPTION:
XS GIS Cut Line= 3
      1372305.01      6862288.00      1372415.35      6862298.12
      1372655.01      6862037.99
#Sta/Elev= 30
  4889.2 2155.57  4899.2 2154.70  4909.3 2152.16  4929.4 2151.65  4933.2 2150.65
  4939.2 2149.08  4944.2 2149.62  4949.4 2148.03  4959.5 2146.84  5003.4 2144.64
  5006.9 2143.59  5021.1 2143.23  5025.9 2141.33  5026.1 2140.83  5029.6 2140.83
  5029.9 2141.33  5035.3 2141.40  5042.1 2144.83  5049.4 2145.40  5056.2 2144.71
  5077.8 2144.99  5098.8 2144.02  5127.1 2144.67  5176.9 2147.28  5190.6 2149.53
  5200.1 2150.06  5219.0 2151.69  5247.4 2152.57  5275.7 2154.48  5353.7 2155.76
#Mann=5,-1,0
  4889.2    0.07       0  4933.2    0.16       0  5025.9    0.07       0
  5029.9    0.16       0  5200.1   0.035       0
Bank Sta=5025.9,5029.9
Exp/Cntr=0.3,0.1

Type RM Length L Ch R = 1,4781,496,496,496
BEGIN DESCRIPTION:
Sweetwater Creek Trib 27 T8_3 7.0
END DESCRIPTION:
XS GIS Cut Line= 3
      1372455.05      6862688.00      1372615.75      6862697.71
      1372705.02      6862637.99
#Sta/Elev= 30
  4839.0 2151.99  4842.3 2151.98  4849.0 2151.92  4869.0 2150.79  4879.0 2147.34
  4889.0 2144.22  4918.0 2142.80  4923.0 2144.21  4929.1 2143.49  4939.1 2141.86
  4949.2 2139.74  4959.2 2139.11  4969.2 2139.34  4979.2 2138.91  4989.2 2138.19
  4995.1 2136.84  4995.4 2136.34  4998.9 2136.34  4999.1 2136.84  5002.6 2136.84
  5006.8 2137.77  5012.8 2138.48  5021.8 2138.97  5035.2 2140.75  5042.8 2141.20
  5057.6 2143.79  5071.3 2146.00  5078.9 2146.51  5084.9 2147.50  5107.4 2147.76
#Mann=5,-1,0
  4839.0    0.16       0  4842.3    0.07       0  4995.1    0.07       0
  4999.1    0.07       0  5057.6   0.035       0
Bank Sta=4995.1,4999.1
Exp/Cntr=0.3,0.1

Type RM Length L Ch R = 1,4285,603,603,603
BEGIN DESCRIPTION:
Sweetwater Creek Trib 27 T8_3 6.0
END DESCRIPTION:
XS GIS Cut Line= 3
      1372905.01      6862987.99      1373060.23      6862837.51
      1373055.00      6862688.00
#Sta/Elev= 30
  4783.8 2146.49  4790.9 2146.72  4812.0 2145.86  4819.2 2146.25  4833.3 2145.42
  4854.4 2145.53  4868.6 2144.07  4887.3 2143.38  4889.9 2143.37  4896.9 2142.06
  4925.2 2139.79  4932.3 2141.62  4939.3 2140.38  4946.5 2141.69  4951.2 2140.90
  4967.6 2139.68  4981.7 2136.95  5002.3 2135.52  5005.6 2134.33  5010.6 2135.54
  5017.5 2133.71  5017.8 2133.21  5021.3 2133.21  5021.5 2133.71  5029.5 2135.99
  5069.5 2138.30  5079.6 2139.51  5100.5 2142.99  5129.6 2145.82  5149.6 2146.51
#Mann=6,-1,0
  4783.8    0.07       0  4887.3   0.035       0  4951.2    0.07       0
  5017.5    0.07       0  5021.5    0.07       0  5100.5   0.035       0
Bank Sta=5017.5,5021.5
Exp/Cntr=0.3,0.1

Type RM Length L Ch R = 1,3682,358,358,358
BEGIN DESCRIPTION:
Sweetwater Creek Trib 27 T8_3 5.0
END DESCRIPTION:
XS GIS Cut Line= 3
      1373383.26      6863341.20      1373521.48      6863021.07
      1373513.42      6862597.74
#Sta/Elev= 30
  4651.3 2141.80  4827.5 2141.06  4845.2 2141.17  4861.7 2141.87  4905.3 2141.50
  4921.1 2139.59  4938.0 2138.30  4950.1 2134.63  4981.6 2131.95  5004.0 2131.43
  5021.1 2129.95  5021.3 2129.45  5024.8 2129.45  5025.1 2129.95  5043.1 2132.19
  5063.1 2133.44  5072.8 2134.97  5077.8 2134.36  5083.1 2136.47  5128.4 2137.68
  5203.1 2138.21  5223.1 2138.86  5273.1 2141.56  5283.1 2142.89  5293.1 2142.69
  5323.1 2144.05  5373.1 2144.48  5393.1 2145.90  5403.1 2145.35  5423.4 2146.01
#Mann=5,-1,0
  4651.3   0.045       0  4827.5    0.07       0  5021.1    0.07       0
  5025.1    0.07       0  5128.4   0.035       0
Bank Sta=5021.1,5025.1
Exp/Cntr=0.3,0.1

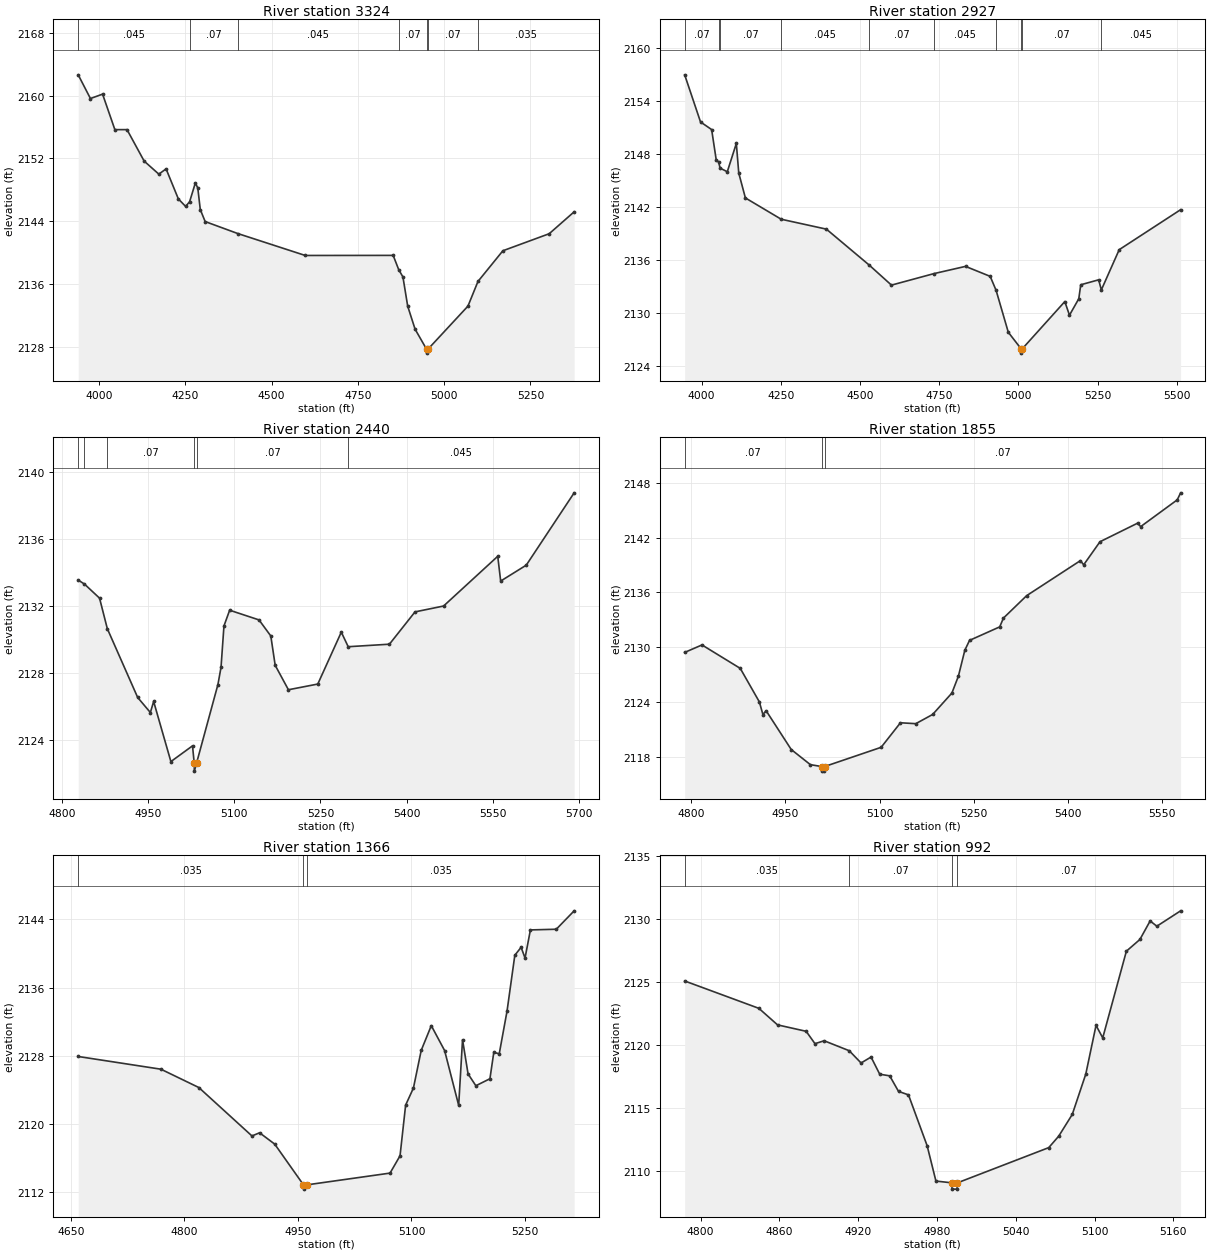
Type RM Length L Ch R = 1,3324,397,397,397
BEGIN DESCRIPTION:
Sweetwater Creek Trib 27 T8_3 4.0
END DESCRIPTION:
XS GIS Cut Line= 3
      1373054.98      6863838.02      1373821.48      6863105.13
      1373905.00      6862738.01
#Sta/Elev= 30
  3939.5 2162.65  3974.9 2159.63  4010.1 2160.19  4045.7 2155.67  4080.9 2155.67
  4130.6 2151.66  4173.1 2150.00  4194.1 2150.67  4229.7 2146.84  4250.7 2145.89
  4262.3 2146.49  4279.0 2148.89  4286.0 2148.23  4293.2 2145.49  4307.3 2143.96
  4402.0 2142.43  4597.3 2139.64  4852.1 2139.65  4868.1 2137.84  4880.4 2136.90
  4894.2 2133.18  4915.6 2130.25  4948.8 2127.70  4949.1 2127.20  4952.9 2127.70
  5068.8 2133.19  5097.8 2136.33  5170.0 2140.24  5304.2 2142.41  5376.5 2145.20
#Mann=7,-1,0
  3939.5   0.045       0  4262.3    0.07       0  4402.0   0.045       0
  4868.1    0.07       0  4948.8    0.07       0  4952.9    0.07       0
  5097.8   0.035       0
Bank Sta=4948.8,4952.9
Exp/Cntr=0.3,0.1

Type RM Length L Ch R = 1,2927,487,487,487
BEGIN DESCRIPTION:
Sweetwater Creek Trib 27 T8_3 3.0
END DESCRIPTION:
XS GIS Cut Line= 3
      1373304.97      6863988.03      1374104.87      6863303.05
      1374405.00      6862888.00
#Sta/Elev= 30
  3946.9 2156.96  3996.9 2151.63  4032.0 2150.77  4046.3 2147.38  4054.1 2147.09
  4058.7 2146.41  4081.4 2146.00  4109.9 2149.20  4117.6 2145.85  4138.5 2143.04
  4251.6 2140.63  4394.2 2139.51  4529.2 2135.45  4599.5 2133.18  4733.5 2134.48
  4833.3 2135.30  4911.2 2134.17  4929.9 2132.58  4968.3 2127.85  5008.5 2125.99
  5008.7 2125.49  5012.7 2125.99  5146.7 2131.32  5161.4 2129.78  5190.8 2131.64
  5197.0 2133.22  5253.5 2133.78  5262.0 2132.64  5318.4 2137.19  5512.2 2141.71
#Mann=10,-1,0
  3946.9    0.07       0  4054.1   0.045       0  4058.7    0.07       0
  4251.6   0.045       0  4529.2    0.07       0  4733.5   0.045       0
  4929.9    0.07       0  5008.5    0.07       0  5012.7    0.07       0
  5262.0   0.045       0
Bank Sta=5008.5,5012.7
Exp/Cntr=0.3,0.1

Type RM Length L Ch R = 1,2440,585,585,585
BEGIN DESCRIPTION:
Sweetwater Creek Trib 27 T8_3 2.2
END DESCRIPTION:
XS GIS Cut Line= 3
      1374280.98      6863792.25      1374348.93      6863661.65
      1374497.34      6862961.83
#Sta/Elev= 30
  4828.7 2133.56  4839.6 2133.32  4865.8 2132.48  4879.3 2130.66  4932.1 2126.55
  4954.2 2125.65  4959.9 2126.31  4989.9 2122.72  5027.5 2123.66  5030.4 2122.65
  5030.7 2122.15  5034.7 2122.65  5071.7 2127.32  5077.1 2128.35  5082.2 2130.82
  5092.1 2131.76  5143.2 2131.18  5163.7 2130.22  5171.3 2128.47  5194.3 2127.01
  5245.4 2127.35  5286.3 2130.45  5298.3 2129.58  5370.0 2129.73  5414.5 2131.66
  5464.2 2132.01  5558.4 2134.98  5563.5 2133.50  5608.0 2134.45  5691.3 2138.77
#Mann=6,-1,0
  4828.7    0.07       0  4839.6   0.045       0  4879.3    0.07       0
  5030.4    0.07       0  5034.7    0.07       0  5298.3   0.045       0
Bank Sta=5030.4,5034.7
Exp/Cntr=0.3,0.1

Type RM Length L Ch R = 1,1855,489,489,489
BEGIN DESCRIPTION:
Sweetwater Creek Trib 27 T8_3 2.1
END DESCRIPTION:
XS GIS Cut Line= 3
      1374832.13      6863595.18      1374794.95      6863387.89
      1374665.38      6862822.75
#Sta/Elev= 30
  4789.4 2129.42  4817.0 2130.24  4878.0 2127.67  4908.4 2124.00  4914.1 2122.61
  4919.2 2123.03  4959.2 2118.78  4989.7 2117.12  5007.9 2116.91  5008.2 2116.41
  5012.0 2116.41  5012.3 2116.91  5102.5 2119.02  5133.3 2121.71  5157.7 2121.61
  5184.6 2122.62  5215.3 2124.97  5225.6 2126.81  5235.9 2129.66  5243.4 2130.74
  5291.5 2132.22  5297.4 2133.18  5334.4 2135.64  5420.1 2139.48  5425.3 2139.02
  5451.3 2141.55  5511.1 2143.58  5516.2 2143.21  5574.4 2146.14  5579.8 2146.91
#Mann=3,-1,0
  4789.4    0.07       0  5007.9    0.07       0  5012.3    0.07       0
Bank Sta=5007.9,5012.3
Exp/Cntr=0.3,0.1

Type RM Length L Ch R = 1,1366,374,374,374
BEGIN DESCRIPTION:
Sweetwater Creek Trib 27 T8_3 2.0
END DESCRIPTION:
XS GIS Cut Line= 3
      1375153.78      6863526.96      1375179.99      6863187.57
      1375256.17      6862881.93
#Sta/Elev= 30
  4659.6 2127.91  4768.9 2126.42  4819.0 2124.27  4889.2 2118.59  4899.3 2118.96
  4919.3 2117.63  4957.3 2112.85  4957.6 2112.35  4961.7 2112.85  5071.7 2114.23
  5084.9 2116.26  5092.3 2122.21  5102.6 2124.21  5112.9 2128.63  5126.2 2131.53
  5143.8 2128.61  5162.4 2122.18  5167.5 2129.88  5174.8 2125.87  5185.1 2124.48
  5203.7 2125.30  5208.8 2128.39  5216.0 2128.23  5226.3 2133.23  5236.6 2139.79
  5244.9 2140.72  5250.1 2139.46  5257.2 2142.76  5291.4 2142.84  5315.0 2145.00
#Mann=3,-1,0
  4659.6   0.035       0  4957.3   0.035       0  4961.7   0.035       0
Bank Sta=4957.3,4961.7
Exp/Cntr=0.3,0.1

Type RM Length L Ch R = 1,992,497,497,497
BEGIN DESCRIPTION:
Sweetwater Creek Trib 27 T8_3 1.0
END DESCRIPTION:
XS GIS Cut Line= 3
      1375355.01      6863437.99      1375514.79      6863298.50
      1375555.01      6863137.96
#Sta/Elev= 30
  4787.9 2125.06  4844.4 2122.89  4858.6 2121.58  4880.4 2121.07  4887.1 2120.09
  4894.1 2120.32  4913.2 2119.53  4922.2 2118.56  4929.8 2119.03  4936.4 2117.67
  4944.0 2117.54  4950.7 2116.31  4958.3 2116.03  4972.5 2112.00  4979.2 2109.20
  4991.2 2109.06  4991.5 2108.56  4995.3 2108.56  4995.6 2109.06  5065.1 2111.85
  5072.7 2112.76  5083.0 2114.48  5093.3 2117.68  5101.1 2121.54  5106.2 2120.55
  5124.2 2127.42  5134.5 2128.35  5142.3 2129.82  5147.4 2129.40  5165.5 2130.62
#Mann=4,-1,0
  4787.9   0.035       0  4913.2    0.07       0  4991.2    0.07       0
  4995.6    0.07       0
Bank Sta=4991.2,4995.6
Exp/Cntr=0.3,0.1

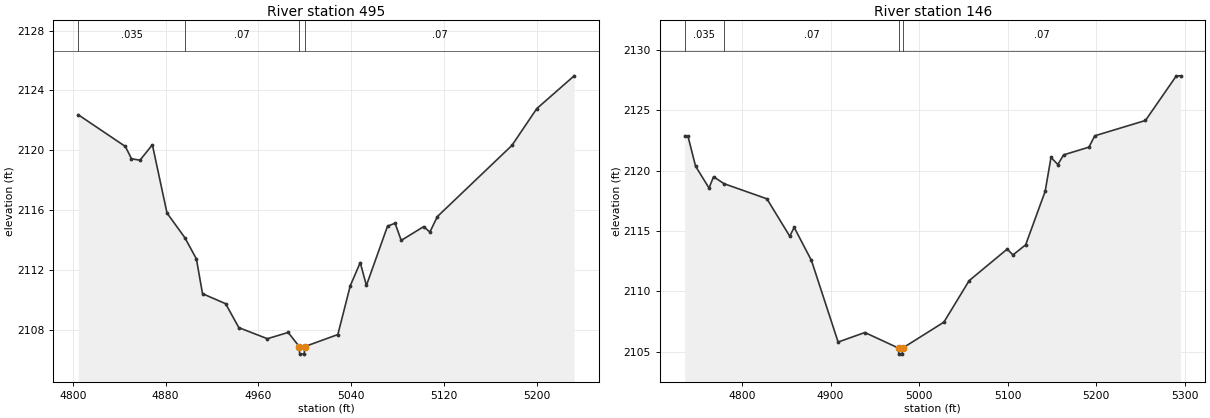
Type RM Length L Ch R = 1,495,349,349,349
BEGIN DESCRIPTION:
Sweetwater Creek Trib 27 T8_3 2410
END DESCRIPTION:
XS GIS Cut Line= 3
      1375604.97      6863738.01      1375788.51      6863671.26
      1376005.05      6863587.98
#Sta/Elev= 30
  4804.7 2122.38  4845.3 2120.26  4850.6 2119.44  4857.9 2119.34  4868.6 2120.37
  4881.2 2115.81  4896.6 2114.16  4906.5 2112.75  4911.8 2110.42  4931.7 2109.75
  4943.1 2108.15  4967.7 2107.41  4985.6 2107.83  4995.2 2106.88  4995.5 2106.38
  4999.4 2106.38  4999.8 2106.88  5028.4 2107.69  5039.1 2110.95  5047.7 2112.50
  5053.0 2110.97  5071.2 2114.93  5077.7 2115.13  5083.0 2113.98  5102.3 2114.90
  5107.7 2114.54  5114.1 2115.57  5178.4 2120.33  5199.8 2122.79  5232.0 2124.98
#Mann=4,-1,0
  4804.7   0.035       0  4896.6    0.07       0  4995.2    0.07       0
  4999.8    0.07       0
Bank Sta=4995.2,4999.8
Exp/Cntr=0.3,0.1

Type RM Length L Ch R = 1,146,0,0,0
BEGIN DESCRIPTION:
Sweetwater Creek Trib 27 T8_3 4500
END DESCRIPTION:
XS GIS Cut Line= 3
      1375672.79      6863939.98      1375935.91      6863968.87
      1376126.26      6863743.37
#Sta/Elev= 30
  4735.3 2122.89  4738.9 2122.89  4747.6 2120.37  4762.8 2118.56  4767.9 2119.50
  4779.8 2118.92  4828.1 2117.67  4853.9 2114.57  4858.9 2115.30  4878.4 2112.56
  4908.5 2105.80  4938.7 2106.59  4976.7 2105.30  4977.0 2104.80  4980.9 2104.80
  4981.3 2105.30  5027.9 2107.45  5056.4 2110.89  5099.3 2113.50  5105.9 2113.02
  5120.2 2113.86  5142.2 2118.29  5148.8 2121.10  5156.5 2120.51  5163.0 2121.31
  5191.6 2121.95  5198.2 2122.89  5255.4 2124.16  5290.3 2127.86  5295.1 2127.86
#Mann=4,-1,0
  4735.3   0.035       0  4779.8    0.07       0  4976.7    0.07       0
  4981.3    0.07       0
Bank Sta=4976.7,4981.3
Exp/Cntr=0.3,0.1

Chan Stop Cuts=-1