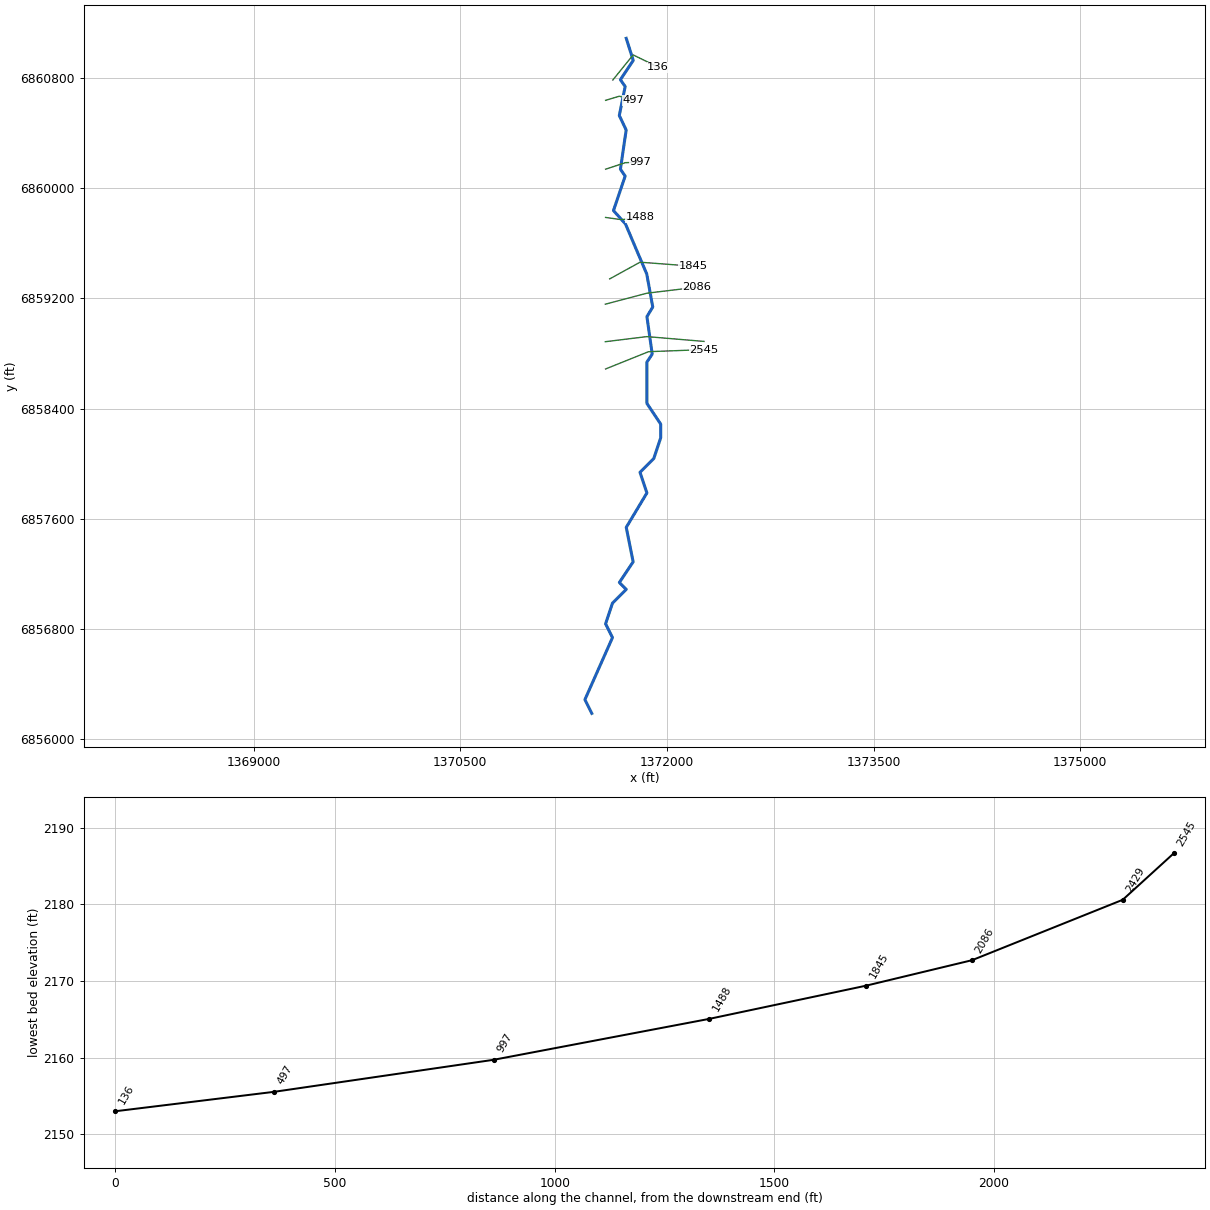
--- Sweetwater Creek Trib 27 T8_3T.prj (project) ---

Proj Title=Sweetwater Creek Trib 27 T8_3T Base Level Engineering
Current Plan=p01
Default Exp/Contr=0.3,0.1
English Units
Geom File=g01
Flow File=f01
Plan File=p01
BEGIN DESCRIPTION:
Sweetwater Creek Trib 27 T8_3T
END DESCRIPTION:

--- Sweetwater Creek Trib 27 T8_3T.p01 (plan) ---

Plan Title=Multiple Run
Short Identifier=Multiple
Geom File=g01
Flow File=f01
Subcritical Flow
K Sum by GR= 0
Std Step Tol= 0.01
Critical Tol= 0.01
Num of Std Step Trials= 20
Max Error Tol= 0.3
Flow Tol Ratio= 0.001
Split Flow NTrial= 30
Split Flow Tol= 0.02
Split Flow Ratio= 0.02
Log Output Level= 0
Friction Slope Method= 1
Unsteady Friction Slope Method= 2
Unsteady Bridges Friction Slope Method= 1
Parabolic Critical Depth
Global Vel Dist=  1 , 1 , 1
Global Log Level= 0
CheckData=True
Encroach Param= -1, 0, 0, 0
BEGIN DESCRIPTION:
Multiple Run
END DESCRIPTION:

--- Sweetwater Creek Trib 27 T8_3T.f01 (steady flow) ---

Flow Title=Multiple
Number of Profiles=7
Profile Names=10-year,25-year,50-year,1pct_min,100-year,1pct_plu,500-year
River Rch & RM= Sweetwater Creek,Reach-1,2545
     149     205     251     153     305     609     458
Boundary for River Rch & Prof#=Sweetwater Creek,Reach-1,1
Up Type=0
Dn Type=3
Dn Slope=0.005
Boundary for River Rch & Prof#=Sweetwater Creek,Reach-1,2
Up Type=0
Dn Type=3
Dn Slope=0.005
Boundary for River Rch & Prof#=Sweetwater Creek,Reach-1,3
Up Type=0
Dn Type=3
Dn Slope=0.005
Boundary for River Rch & Prof#=Sweetwater Creek,Reach-1,4
Up Type=0
Dn Type=3
Dn Slope=0.005
Boundary for River Rch & Prof#=Sweetwater Creek,Reach-1,5
Up Type=0
Dn Type=3
Dn Slope=0.005
Boundary for River Rch & Prof#=Sweetwater Creek,Reach-1,6
Up Type=0
Dn Type=3
Dn Slope=0.005
Boundary for River Rch & Prof#=Sweetwater Creek,Reach-1,7
Up Type=0
Dn Type=3
Dn Slope=0.005

--- Sweetwater Creek Trib 27 T8_3T.g01 (geometry) ---

Geom Title=Existing Conditions

River Reach=Sweetwater Creek,Reach-1
Reach XY= 30
      1371455.00      6856188.00      1371405.00      6856288.00
      1371605.00      6856738.00      1371555.00      6856838.00
      1371605.00      6856988.00      1371705.00      6857088.00
      1371655.00      6857138.00      1371755.00      6857288.00
      1371705.00      6857538.00      1371855.00      6857788.00
      1371805.00      6857938.00      1371905.00      6858038.00
      1371955.00      6858188.00      1371955.00      6858288.00
      1371855.00      6858438.00      1371855.00      6858738.00
      1371893.42      6858795.99      1371855.18      6859068.02
      1371897.44      6859138.00      1371853.78      6859377.50
      1371699.45      6859740.43      1371612.33      6859837.90
      1371697.21      6860088.10      1371662.79      6860137.90
      1371704.48      6860422.78      1371654.54      6860527.82
      1371697.19      6860738.10      1371662.56      6860788.00
      1371755.83      6860927.92      1371705.00      6861088.00

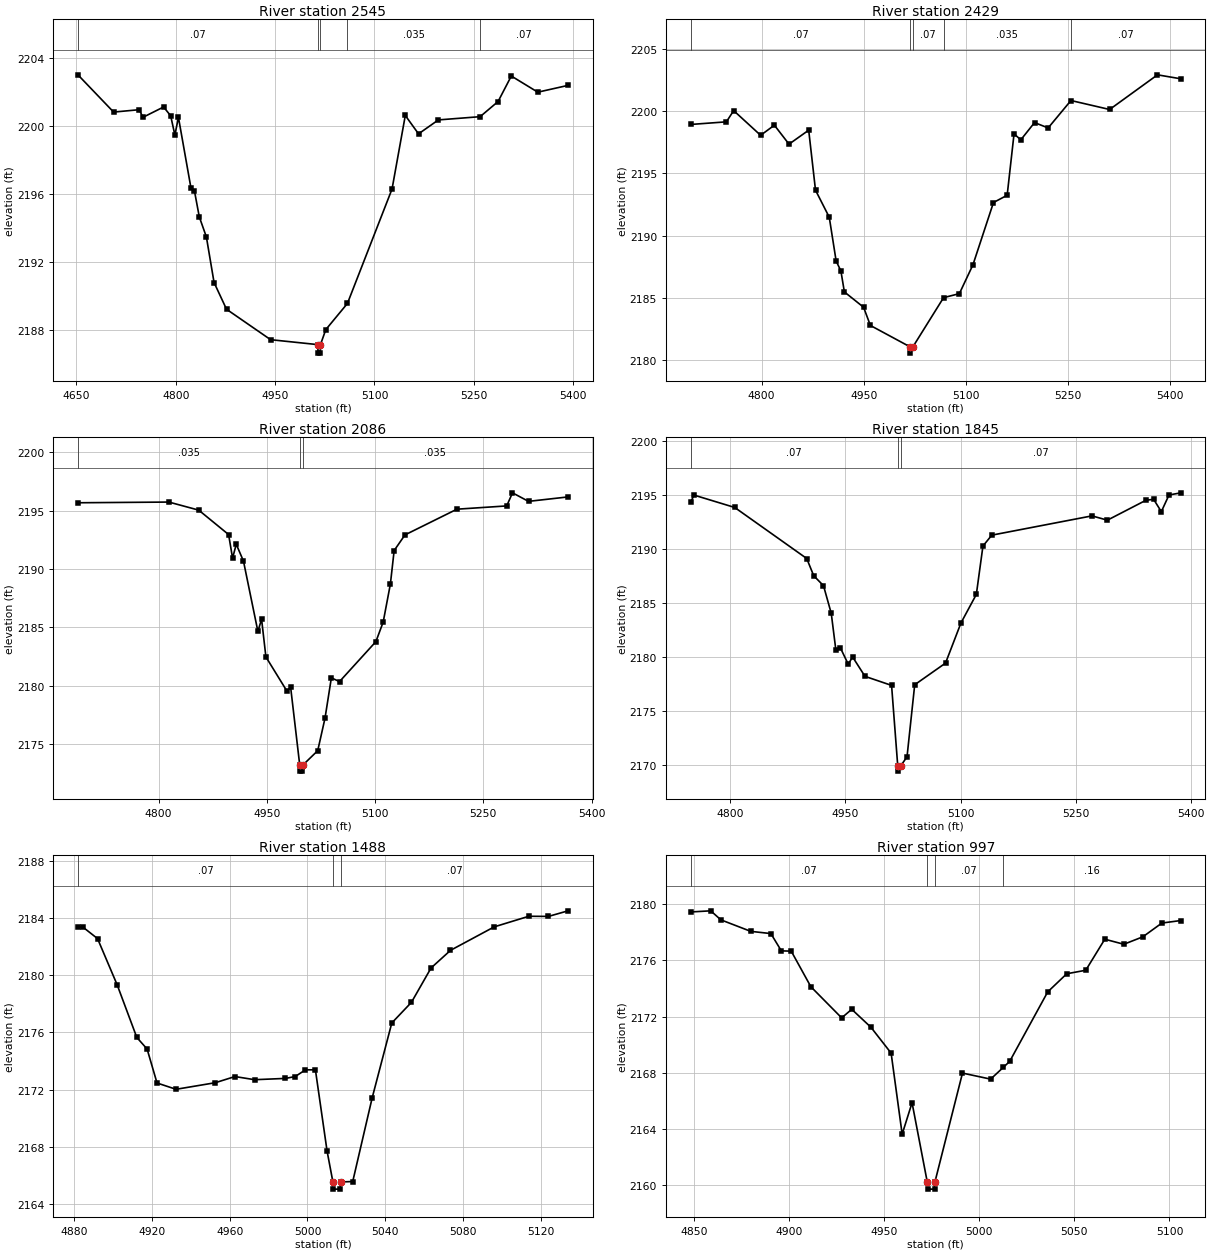
Type RM Length L Ch R = 1,2545,116,116,116
BEGIN DESCRIPTION:
Sweetwater Creek Trib 27 T8_3T 4.0
END DESCRIPTION:
XS GIS Cut Line= 3
      1371554.99      6858688.00      1371866.50      6858813.33
      1372270.63      6858828.58
#Sta/Elev= 30
  4652.2 2203.00  4706.1 2200.81  4744.9 2200.95  4750.3 2200.50  4781.6 2201.11
  4792.3 2200.59  4798.6 2199.46  4804.0 2200.50  4822.8 2196.37  4828.2 2196.17
  4835.5 2194.65  4846.2 2193.47  4857.8 2190.79  4876.6 2189.22  4943.2 2187.43
  5014.5 2187.14  5014.8 2186.64  5018.3 2186.64  5018.5 2187.14  5026.5 2188.02
  5059.2 2189.56  5126.6 2196.29  5146.6 2200.61  5166.6 2199.53  5196.6 2200.35
  5259.6 2200.54  5286.7 2201.43  5306.7 2202.93  5346.7 2201.98  5392.4 2202.38
#Mann=5,-1,0
  4652.2    0.07       0  5014.5    0.07       0  5018.5    0.07       0
  5059.2   0.035       0  5259.6    0.07       0
Bank Sta=5014.5,5018.5
Exp/Cntr=0.3,0.1

Type RM Length L Ch R = 1,2429,343,343,343
BEGIN DESCRIPTION:
Sweetwater Creek Trib 27 T8_3T 4502
END DESCRIPTION:
XS GIS Cut Line= 3
      1371553.12      6858885.84      1371854.85      6858922.94
      1372269.28      6858888.01
#Sta/Elev= 30
  4696.0 2198.93  4748.3 2199.14  4759.0 2200.04  4798.6 2198.06  4818.8 2198.87
  4840.3 2197.35  4869.2 2198.47  4879.2 2193.66  4899.4 2191.49  4909.5 2187.98
  4916.5 2187.18  4921.6 2185.50  4949.8 2184.27  4959.8 2182.81  5018.2 2181.09
  5018.5 2180.59  5022.2 2181.09  5067.3 2185.04  5090.5 2185.36  5110.5 2187.68
  5140.6 2192.67  5160.7 2193.25  5170.8 2198.17  5180.8 2197.70  5200.9 2199.08
  5220.9 2198.65  5254.4 2200.85  5311.2 2200.13  5381.5 2202.91  5415.9 2202.59
#Mann=5,-1,0
  4696.0    0.07       0  5018.2    0.07       0  5022.2    0.07       0
  5067.3   0.035       0  5254.4    0.07       0
Bank Sta=5018.2,5022.2
Exp/Cntr=0.3,0.1

Type RM Length L Ch R = 1,2086,241,241,241
BEGIN DESCRIPTION:
Sweetwater Creek Trib 27 T8_3T 4503
END DESCRIPTION:
XS GIS Cut Line= 3
      1371553.17      6859158.20      1371854.63      6859237.82
      1372219.38      6859281.89
#Sta/Elev= 30
  4688.2 2195.67  4814.2 2195.73  4855.6 2195.04  4897.0 2192.95  4902.5 2190.93
  4907.6 2192.12  4917.6 2190.68  4937.6 2184.66  4942.7 2185.71  4948.7 2182.48
  4977.8 2179.56  4983.0 2179.87  4995.6 2173.21  4995.9 2172.71  4999.4 2172.71
  4999.6 2173.21  5020.5 2174.46  5030.6 2177.24  5039.4 2180.69  5050.7 2180.37
  5101.1 2183.79  5111.2 2185.46  5121.2 2188.72  5126.4 2191.58  5141.4 2192.92
  5213.4 2195.12  5282.4 2195.40  5290.4 2196.52  5312.6 2195.79  5367.4 2196.17
#Mann=3,-1,0
  4688.2   0.035       0  4995.6   0.035       0  4999.6   0.035       0
Bank Sta=4995.6,4999.6
Exp/Cntr=0.3,0.1

Type RM Length L Ch R = 1,1845,357,357,357
BEGIN DESCRIPTION:
Sweetwater Creek Trib 27 T8_3T 3.0
END DESCRIPTION:
XS GIS Cut Line= 3
      1371584.88      6859341.78      1371805.01      6859463.00
      1372190.41      6859433.83
#Sta/Elev= 30
  4748.7 2194.38  4752.9 2195.02  4805.9 2193.87  4899.6 2189.13  4908.7 2187.53
  4921.4 2186.61  4931.5 2184.04  4937.5 2180.63  4943.2 2180.86  4953.6 2179.32
  4959.3 2179.99  4975.4 2178.19  5010.0 2177.35  5018.0 2169.89  5018.3 2169.39
  5022.0 2169.89  5030.1 2170.72  5040.1 2177.41  5080.2 2179.42  5100.3 2183.15
  5120.3 2185.80  5128.9 2190.29  5140.4 2191.30  5270.8 2193.09  5290.8 2192.69
  5341.0 2194.54  5351.0 2194.63  5361.0 2193.48  5371.0 2195.03  5386.5 2195.23
#Mann=3,-1,0
  4748.7    0.07       0  5018.0    0.07       0  5022.0    0.07       0
Bank Sta=5018,5022
Exp/Cntr=0.3,0.1

Type RM Length L Ch R = 1,1488,491,491,491
BEGIN DESCRIPTION:
Sweetwater Creek Trib 27 T8_3T 2.0
END DESCRIPTION:
XS GIS Cut Line= 3
      1371554.98      6859788.00      1371671.92      6859771.52
      1371805.01      6859788.00
#Sta/Elev= 30
  4881.9 2183.36  4884.4 2183.36  4892.0 2182.55  4902.1 2179.32  4912.2 2175.65
  4917.5 2174.84  4922.6 2172.47  4932.4 2172.03  4952.6 2172.49  4962.7 2172.92
  4972.8 2172.70  4988.7 2172.79  4993.7 2172.92  4999.0 2173.39  5004.1 2173.39
  5010.1 2167.72  5013.1 2165.56  5013.4 2165.06  5016.9 2165.06  5017.1 2165.56
  5023.3 2165.59  5033.3 2171.43  5043.4 2176.66  5053.5 2178.10  5063.6 2180.50
  5073.6 2181.73  5096.1 2183.37  5113.9 2184.11  5124.0 2184.10  5134.1 2184.49
#Mann=3,-1,0
  4881.9    0.07       0  5013.1    0.07       0  5017.1    0.07       0
Bank Sta=5013.1,5017.1
Exp/Cntr=0.3,0.1

Type RM Length L Ch R = 1,997,500,500,500
BEGIN DESCRIPTION:
Sweetwater Creek Trib 27 T8_3T 1.0
END DESCRIPTION:
XS GIS Cut Line= 3
      1371555.04      6860138.01      1371699.00      6860185.55
      1371804.97      6860188.00
#Sta/Elev= 30
  4848.4 2179.45  4858.9 2179.53  4864.2 2178.89  4879.9 2178.07  4890.5 2177.91
  4896.0 2176.68  4901.2 2176.66  4911.5 2174.13  4927.7 2171.91  4933.0 2172.52
  4943.1 2171.24  4953.7 2169.40  4959.5 2163.63  4964.7 2165.87  4972.7 2160.22
  4973.0 2159.72  4976.5 2159.72  4976.7 2160.22  4991.2 2167.98  5006.0 2167.55
  5012.6 2168.38  5016.0 2168.81  5036.0 2173.76  5046.0 2175.05  5056.0 2175.30
  5066.0 2177.51  5076.0 2177.15  5086.0 2177.68  5096.0 2178.66  5106.0 2178.84
#Mann=4,-1,0
  4848.4    0.07       0  4972.7    0.07       0  4976.7    0.07       0
  5012.6    0.16       0
Bank Sta=4972.7,4976.7
Exp/Cntr=0.3,0.1

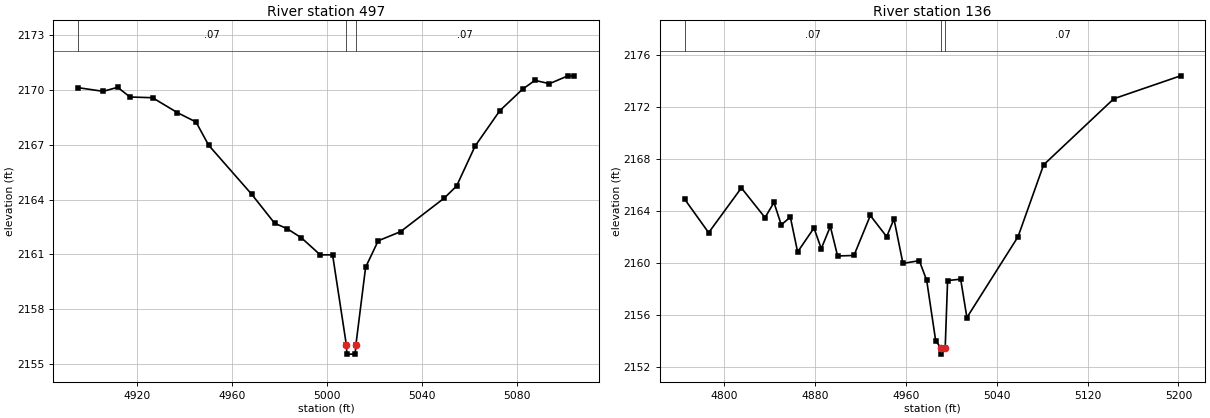
Type RM Length L Ch R = 1,497,361,361,361
BEGIN DESCRIPTION:
Sweetwater Creek Trib 27 T8_3T 2869
END DESCRIPTION:
XS GIS Cut Line= 3
      1371554.98      6860637.99      1371655.18      6860668.02
      1371754.96      6860638.01
#Sta/Elev= 30
  4895.4 2170.14  4905.9 2169.94  4912.0 2170.16  4917.2 2169.63  4926.7 2169.59
  4937.2 2168.77  4945.0 2168.26  4950.3 2166.99  4968.5 2164.29  4978.1 2162.71
  4983.3 2162.42  4989.4 2161.91  4997.3 2160.98  5002.5 2160.98  5008.3 2156.04
  5008.5 2155.54  5012.0 2155.54  5012.3 2156.04  5016.4 2160.30  5021.7 2161.75
  5031.1 2162.25  5049.5 2164.09  5054.7 2164.75  5062.5 2166.94  5072.9 2168.88
  5082.5 2170.06  5087.7 2170.54  5093.8 2170.36  5101.6 2170.79  5104.2 2170.79
#Mann=3,-1,0
  4895.4    0.07       0  5008.3    0.07       0  5012.3    0.07       0
Bank Sta=5008.3,5012.3
Exp/Cntr=0.3,0.1

Type RM Length L Ch R = 1,136,0,0,0
BEGIN DESCRIPTION:
Sweetwater Creek Trib 27 T8_3T 4500
END DESCRIPTION:
XS GIS Cut Line= 3
      1371607.61      6860785.52      1371755.16      6860967.91
      1371936.35      6860878.84
#Sta/Elev= 30
  4765.4 2164.91  4786.5 2162.34  4815.3 2165.78  4836.1 2163.50  4844.0 2164.66
  4850.4 2162.94  4858.4 2163.54  4864.8 2160.86  4879.2 2162.70  4885.6 2161.11
  4893.6 2162.82  4900.0 2160.55  4914.4 2160.59  4928.8 2163.66  4943.2 2162.03
  4949.6 2163.39  4957.5 2159.98  4971.9 2160.19  4978.4 2158.68  4986.3 2154.05
  4990.7 2153.51  4991.0 2153.01  4994.7 2153.51  4996.8 2158.66  5008.3 2158.77
  5013.8 2155.82  5058.8 2162.03  5081.3 2167.55  5143.1 2172.63  5201.9 2174.39
#Mann=3,-1,0
  4765.4    0.07       0  4990.7    0.07       0  4994.7    0.07       0
Bank Sta=4990.7,4994.7
Exp/Cntr=0.3,0.1

Chan Stop Cuts=-1