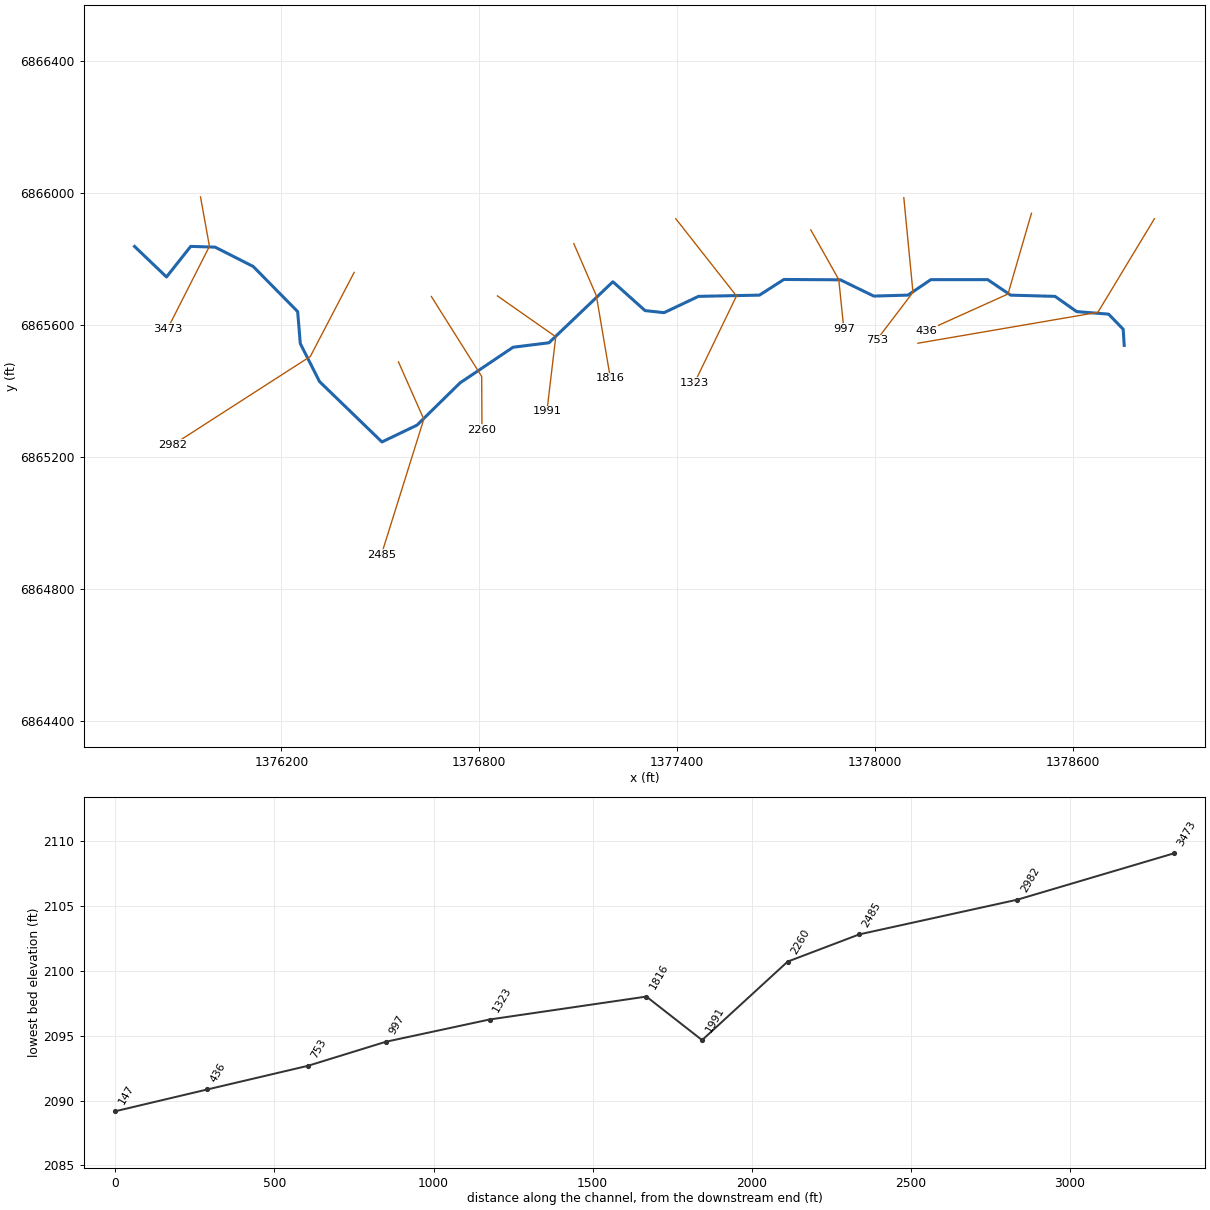
--- Sweetwater Creek Trib 27 T8_4.prj (project) ---

Proj Title=Sweetwater Creek Trib 27 T8_4 Base Level Engineering
Current Plan=p01
Default Exp/Contr=0.3,0.1
English Units
Geom File=g01
Flow File=f01
Plan File=p01
BEGIN DESCRIPTION:
Sweetwater Creek Trib 27 T8_4
END DESCRIPTION:

--- Sweetwater Creek Trib 27 T8_4.p01 (plan) ---

Plan Title=Multiple Run
Short Identifier=Multiple
Geom File=g01
Flow File=f01
Subcritical Flow
K Sum by GR= 0
Std Step Tol= 0.01
Critical Tol= 0.01
Num of Std Step Trials= 20
Max Error Tol= 0.3
Flow Tol Ratio= 0.001
Split Flow NTrial= 30
Split Flow Tol= 0.02
Split Flow Ratio= 0.02
Log Output Level= 0
Friction Slope Method= 1
Unsteady Friction Slope Method= 2
Unsteady Bridges Friction Slope Method= 1
Parabolic Critical Depth
Global Vel Dist=  1 , 1 , 1
Global Log Level= 0
CheckData=True
Encroach Param= -1, 0, 0, 0
BEGIN DESCRIPTION:
Multiple Run
END DESCRIPTION:

--- Sweetwater Creek Trib 27 T8_4.f01 (steady flow) ---

Flow Title=Multiple
Number of Profiles=7
Profile Names=10-year,25-year,50-year,1pct_min,100-year,1pct_plu,500-year
River Rch & RM= Sweetwater Creek,Reach-1,3473
     272     387     483     301     600    1198     938
Boundary for River Rch & Prof#=Sweetwater Creek,Reach-1,1
Up Type=0
Dn Type=3
Dn Slope=0.005
Boundary for River Rch & Prof#=Sweetwater Creek,Reach-1,2
Up Type=0
Dn Type=3
Dn Slope=0.005
Boundary for River Rch & Prof#=Sweetwater Creek,Reach-1,3
Up Type=0
Dn Type=3
Dn Slope=0.005
Boundary for River Rch & Prof#=Sweetwater Creek,Reach-1,4
Up Type=0
Dn Type=3
Dn Slope=0.005
Boundary for River Rch & Prof#=Sweetwater Creek,Reach-1,5
Up Type=0
Dn Type=3
Dn Slope=0.005
Boundary for River Rch & Prof#=Sweetwater Creek,Reach-1,6
Up Type=0
Dn Type=3
Dn Slope=0.005
Boundary for River Rch & Prof#=Sweetwater Creek,Reach-1,7
Up Type=0
Dn Type=3
Dn Slope=0.005

--- Sweetwater Creek Trib 27 T8_4.g01 (geometry) ---

Geom Title=Existing Conditions

River Reach=Sweetwater Creek,Reach-1
Reach XY= 30
      1375755.00      6865838.00      1375851.85      6865745.41
      1375925.26      6865838.10      1375999.36      6865835.78
      1376114.68      6865777.24      1376249.48      6865640.43
      1376257.45      6865543.56      1376315.76      6865428.32
      1376504.91      6865245.28      1376611.05      6865296.12
      1376741.79      6865424.37      1376902.58      6865532.46
      1377011.17      6865545.86      1377204.99      6865730.92
      1377302.57      6865643.43      1377360.02      6865637.17
      1377464.66      6865686.62      1377649.47      6865690.38
      1377723.27      6865737.79      1377894.49      6865736.78
      1377995.74      6865687.50      1378099.47      6865690.37
      1378168.92      6865737.32      1378341.08      6865737.32
      1378410.94      6865690.27      1378545.33      6865686.61
      1378610.98      6865640.36      1378707.66      6865632.67
      1378751.88      6865587.01      1378755.00      6865538.00

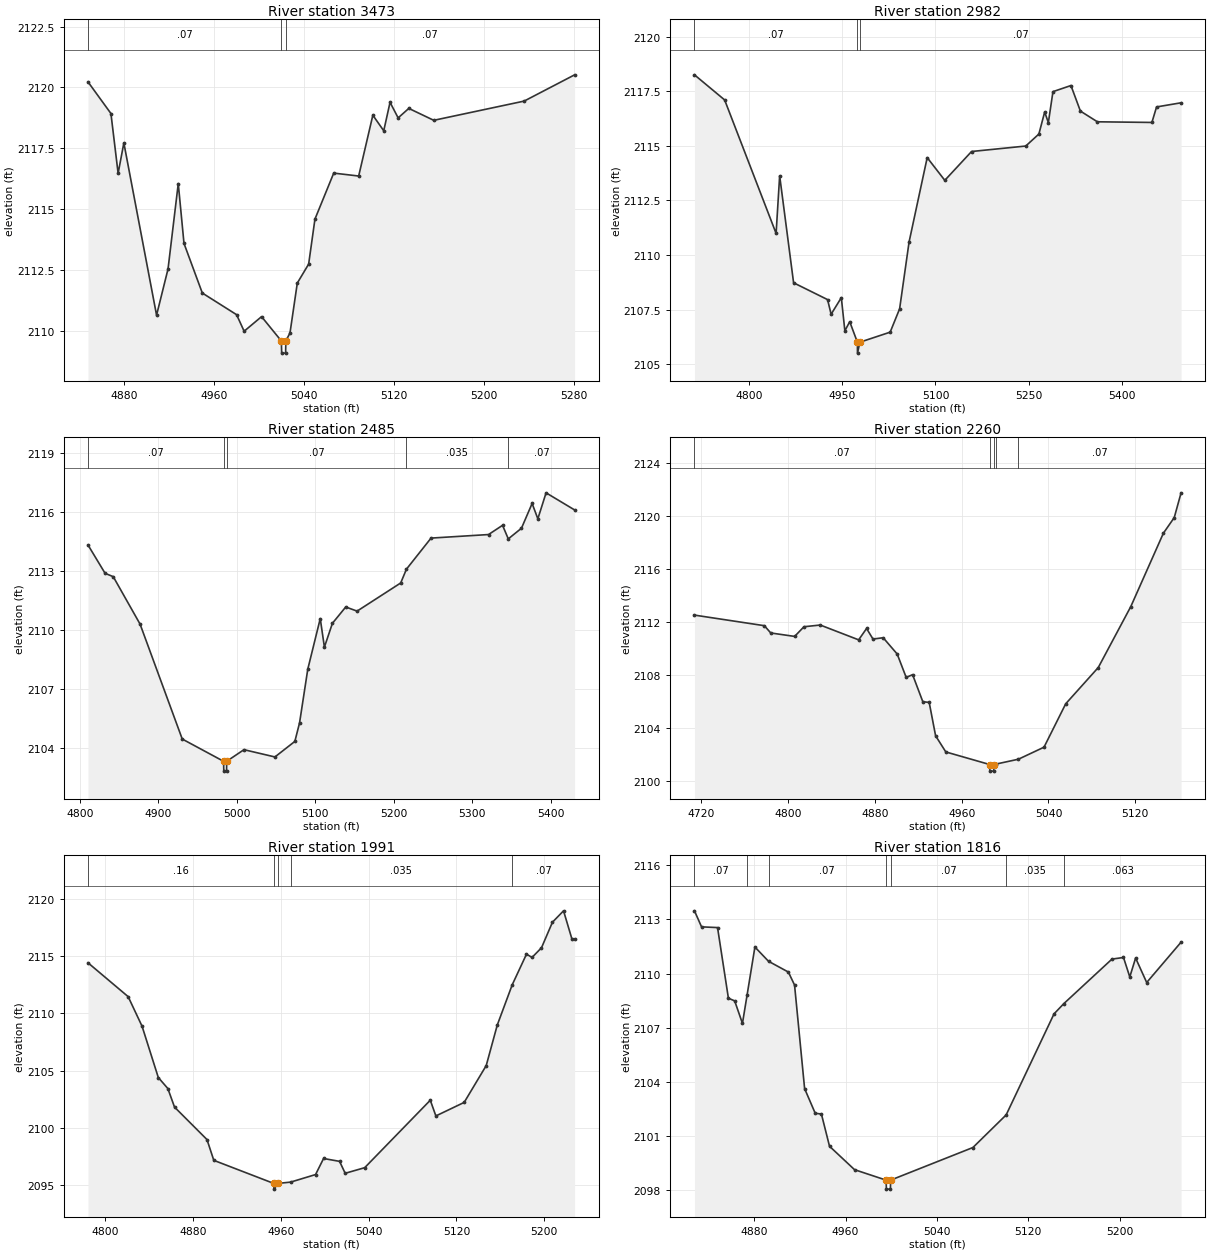
Type RM Length L Ch R = 1,3473,491,491,491
BEGIN DESCRIPTION:
Sweetwater Creek Trib 27 T8_4 4.0
END DESCRIPTION:
XS GIS Cut Line= 3
      1375954.99      6865988.04      1375982.07      6865838.37
      1375854.99      6865587.97
#Sta/Elev= 30
  4847.9 2120.23  4868.3 2118.93  4874.7 2116.47  4879.8 2117.72  4908.9 2110.64
  4919.1 2112.54  4928.2 2116.05  4933.3 2113.59  4949.6 2111.55  4980.1 2110.66
  4986.8 2109.98  5002.3 2110.58  5019.9 2109.58  5020.2 2109.08  5023.7 2109.08
  5023.9 2109.58  5027.6 2109.91  5034.1 2111.96  5044.2 2112.74  5049.8 2114.59
  5066.5 2116.48  5088.7 2116.36  5101.3 2118.86  5111.0 2118.22  5116.6 2119.39
  5123.8 2118.75  5133.3 2119.14  5155.5 2118.65  5235.9 2119.44  5280.8 2120.52
#Mann=3,-1,0
  4847.9    0.07       0  5019.9    0.07       0  5023.9    0.07       0
Bank Sta=5019.9,5023.9
Exp/Cntr=0.3,0.1

Type RM Length L Ch R = 1,2982,497,497,497
BEGIN DESCRIPTION:
Sweetwater Creek Trib 27 T8_4 3.0
END DESCRIPTION:
XS GIS Cut Line= 3
      1376420.75      6865759.22      1376287.89      6865504.48
      1375871.86      6865236.82
#Sta/Elev= 30
  4712.7 2118.25  4761.2 2117.10  4843.9 2110.99  4849.6 2113.63  4872.0 2108.73
  4926.6 2107.96  4932.3 2107.29  4948.7 2108.05  4954.4 2106.53  4962.2 2106.95
  4974.5 2106.01  4974.7 2105.51  4978.5 2106.01  5027.2 2106.47  5042.4 2107.54
  5057.6 2110.60  5086.7 2114.46  5115.0 2113.42  5158.0 2114.74  5245.1 2114.99
  5266.2 2115.54  5275.5 2116.55  5281.4 2116.06  5288.8 2117.48  5317.7 2117.76
  5332.9 2116.59  5360.2 2116.10  5447.8 2116.07  5455.3 2116.78  5494.7 2116.97
#Mann=3,-1,0
  4712.7    0.07       0  4974.5    0.07       0  4978.5    0.07       0
Bank Sta=4974.5,4978.5
Exp/Cntr=0.3,0.1

Type RM Length L Ch R = 1,2485,225,225,225
BEGIN DESCRIPTION:
Sweetwater Creek Trib 27 T8_4 2.0
END DESCRIPTION:
XS GIS Cut Line= 3
      1376555.02      6865487.96      1376631.82      6865314.29
      1376503.18      6864903.25
#Sta/Elev= 30
  4810.1 2114.32  4831.9 2112.88  4842.3 2112.71  4876.5 2110.30  4930.3 2104.46
  4983.0 2103.33  4983.3 2102.83  4986.8 2102.83  4987.0 2103.33  5009.0 2103.92
  5048.5 2103.55  5073.9 2104.34  5079.9 2105.28  5090.4 2108.01  5106.3 2110.58
  5111.6 2109.13  5121.8 2110.34  5138.8 2111.17  5153.3 2110.96  5208.9 2112.39
  5216.2 2113.09  5247.6 2114.67  5320.9 2114.85  5338.8 2115.32  5346.1 2114.63
  5362.9 2115.17  5376.5 2116.43  5383.8 2115.65  5394.3 2116.97  5430.7 2116.10
#Mann=5,-1,0
  4810.1    0.07       0  4983.0    0.07       0  4987.0    0.07       0
  5216.2   0.035       0  5346.1    0.07       0
Bank Sta=4983,4987
Exp/Cntr=0.3,0.1

Type RM Length L Ch R = 1,2260,269,269,269
BEGIN DESCRIPTION:
Sweetwater Creek Trib 27 T8_4 4508
END DESCRIPTION:
XS GIS Cut Line= 3
      1376654.82      6865686.08      1376807.28      6865443.87
      1376808.18      6865281.67
#Sta/Elev= 30
  4713.8 2112.52  4778.2 2111.72  4784.1 2111.17  4806.1 2110.91  4814.7 2111.64
  4829.7 2111.77  4865.1 2110.65  4872.4 2111.51  4878.3 2110.71  4887.7 2110.81
  4900.6 2109.58  4908.9 2107.81  4914.8 2108.02  4924.2 2105.98  4930.1 2105.92
  4936.0 2103.40  4945.4 2102.18  4985.8 2101.23  4986.0 2100.73  4989.5 2100.73
  4989.8 2101.23  4991.5 2101.26  5012.3 2101.63  5035.9 2102.54  5055.9 2105.82
  5085.9 2108.56  5115.9 2113.17  5145.9 2118.71  5155.9 2119.89  5162.2 2121.76
#Mann=5,-1,0
  4713.8    0.07       0  4985.8    0.07       0  4989.8    0.07       0
  4991.5    0.16       0  5012.3    0.07       0
Bank Sta=4985.8,4989.8
Exp/Cntr=0.3,0.1

Type RM Length L Ch R = 1,1991,175,175,175
BEGIN DESCRIPTION:
Sweetwater Creek Trib 27 T8_4 1.0
END DESCRIPTION:
XS GIS Cut Line= 3
      1376855.00      6865688.00      1377031.87      6865564.18
      1377005.00      6865337.97
#Sta/Elev= 30
  4784.1 2114.40  4820.7 2111.45  4833.4 2108.87  4848.2 2104.40  4856.9 2103.44
  4863.0 2101.82  4892.6 2098.99  4898.8 2097.18  4953.4 2095.17  4953.7 2094.67
  4957.4 2095.17  4968.8 2095.28  4991.6 2095.94  4998.9 2097.34  5013.5 2097.09
  5018.6 2096.05  5036.4 2096.54  5096.2 2102.42  5101.3 2101.05  5127.1 2102.23
  5147.2 2105.44  5157.3 2108.98  5170.9 2112.48  5183.9 2115.15  5189.0 2114.87
  5197.6 2115.71  5207.6 2117.94  5217.7 2118.93  5225.3 2116.49  5227.8 2116.49
#Mann=5,-1,0
  4784.1    0.16       0  4953.4   0.035       0  4957.4    0.16       0
  4968.8   0.035       0  5170.9    0.07       0
Bank Sta=4953.4,4957.4
Exp/Cntr=0.3,0.1

Type RM Length L Ch R = 1,1816,493,493,493
BEGIN DESCRIPTION:
Sweetwater Creek Trib 27 T8_4 4503
END DESCRIPTION:
XS GIS Cut Line= 3
      1377086.56      6865846.51      1377154.90      6865688.45
      1377197.46      6865438.35
#Sta/Elev= 30
  4827.8 2113.48  4834.0 2112.59  4848.0 2112.55  4857.5 2108.63  4863.0 2108.48
  4869.8 2107.23  4873.9 2108.82  4880.7 2111.47  4892.6 2110.68  4910.0 2110.08
  4915.4 2109.36  4924.2 2103.61  4933.5 2102.24  4938.9 2102.20  4946.0 2100.41
  4967.9 2099.11  4995.5 2098.53  4995.8 2098.03  4999.3 2098.03  4999.5 2098.53
  5071.5 2100.34  5100.6 2102.15  5142.5 2107.76  5151.1 2108.33  5193.2 2110.80
  5203.3 2110.89  5208.8 2109.81  5213.9 2110.86  5223.6 2109.50  5253.7 2111.74
#Mann=7,-1,0
  4827.8    0.07       0  4873.9   0.035       0  4892.6    0.07       0
  4995.5    0.07       0  4999.5    0.07       0  5100.6   0.035       0
  5151.1   0.063       0
Bank Sta=4995.5,4999.5
Exp/Cntr=0.3,0.1

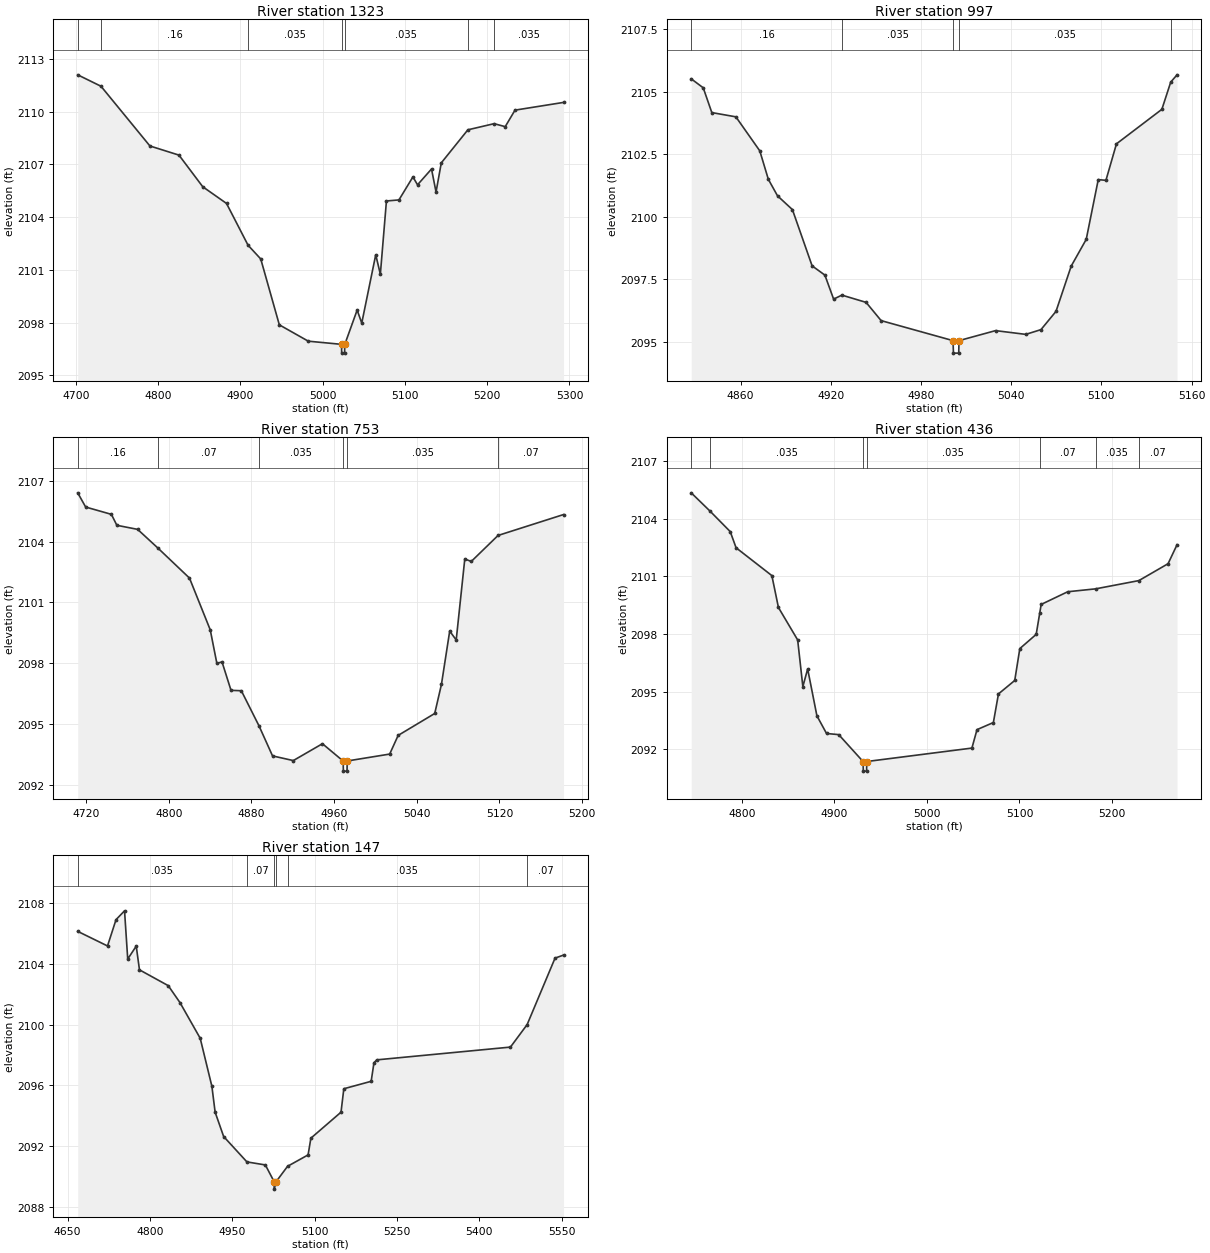
Type RM Length L Ch R = 1,1323,326,326,326
BEGIN DESCRIPTION:
Sweetwater Creek Trib 27 T8_4 4504
END DESCRIPTION:
XS GIS Cut Line= 3
      1377395.64      6865921.97      1377579.64      6865687.81
      1377452.26      6865424.17
#Sta/Elev= 30
  4702.2 2112.10  4730.5 2111.45  4790.0 2108.05  4825.3 2107.53  4854.2 2105.73
  4883.1 2104.78  4909.3 2102.40  4924.7 2101.62  4947.3 2097.87  4982.5 2096.94
  5022.9 2096.76  5023.1 2096.26  5026.6 2096.26  5026.9 2096.76  5041.9 2098.71
  5047.5 2097.97  5064.5 2101.86  5070.1 2100.75  5077.5 2104.92  5092.7 2104.98
  5109.7 2106.29  5115.3 2105.84  5132.3 2106.74  5137.8 2105.43  5144.2 2107.09
  5176.5 2108.97  5208.4 2109.32  5221.9 2109.15  5233.8 2110.09  5292.8 2110.53
#Mann=7,-1,0
  4702.2    0.07       0  4730.5    0.16       0  4909.3   0.035       0
  5022.9   0.035       0  5026.9   0.035       0  5176.5    0.07       0
  5208.4   0.035       0
Bank Sta=5022.9,5026.9
Exp/Cntr=0.3,0.1

Type RM Length L Ch R = 1,997,244,244,244
BEGIN DESCRIPTION:
Sweetwater Creek Trib 27 T8_4 2354
END DESCRIPTION:
XS GIS Cut Line= 3
      1377804.98      6865888.04      1377889.78      6865737.48
      1377905.00      6865587.95
#Sta/Elev= 30
  4827.2 2105.51  4835.2 2105.15  4840.9 2104.16  4856.9 2103.99  4872.8 2102.63
  4878.5 2101.49  4884.6 2100.83  4894.5 2100.28  4907.6 2098.03  4916.1 2097.66
  4921.9 2096.70  4927.4 2096.86  4943.5 2096.57  4953.5 2095.84  5001.3 2095.04
  5001.6 2094.54  5005.1 2094.54  5005.3 2095.04  5029.6 2095.44  5049.7 2095.29
  5059.8 2095.48  5069.8 2096.21  5079.9 2098.02  5089.9 2099.09  5097.9 2101.48
  5103.0 2101.45  5110.0 2102.91  5140.2 2104.29  5146.1 2105.38  5150.3 2105.67
#Mann=5,-1,0
  4827.2    0.16       0  4927.4   0.035       0  5001.3   0.035       0
  5005.3   0.035       0  5146.1    0.07       0
Bank Sta=5001.3,5005.3
Exp/Cntr=0.3,0.1

Type RM Length L Ch R = 1,753,317,317,317
BEGIN DESCRIPTION:
Sweetwater Creek Trib 27 T8_4 4506
END DESCRIPTION:
XS GIS Cut Line= 3
      1378086.89      6865985.71      1378114.64      6865698.85
      1378004.35      6865553.95
#Sta/Elev= 30
  4711.8 2106.40  4719.5 2105.70  4744.4 2105.34  4749.7 2104.80  4769.8 2104.60
  4789.2 2103.69  4820.0 2102.20  4840.1 2099.65  4846.5 2098.00  4851.5 2098.07
  4860.2 2096.67  4870.2 2096.65  4887.3 2094.92  4900.4 2093.44  4920.5 2093.21
  4948.7 2094.04  4968.7 2093.19  4969.0 2092.69  4972.5 2092.69  4972.7 2093.19
  5013.8 2093.53  5022.0 2094.45  5057.4 2095.53  5063.9 2096.96  5071.9 2099.59
  5078.2 2099.15  5086.5 2103.14  5092.8 2103.02  5118.7 2104.30  5182.1 2105.33
#Mann=6,-1,0
  4711.8    0.16       0  4789.2    0.07       0  4887.3   0.035       0
  4968.7   0.035       0  4972.7   0.035       0  5118.7    0.07       0
Bank Sta=4968.7,4972.7
Exp/Cntr=0.3,0.1

Type RM Length L Ch R = 1,436,289,289,289
BEGIN DESCRIPTION:
Sweetwater Creek Trib 27 T8_4 4505
END DESCRIPTION:
XS GIS Cut Line= 3
      1378473.83      6865938.52      1378402.67      6865693.75
      1378156.16      6865582.62
#Sta/Elev= 30
  4745.1 2105.35  4765.4 2104.40  4787.3 2103.33  4793.6 2102.49  4832.3 2101.04
  4839.4 2099.38  4860.2 2097.69  4865.8 2095.26  4871.0 2096.18  4881.0 2093.74
  4891.4 2092.82  4904.6 2092.76  4930.9 2091.36  4931.2 2090.86  4934.7 2090.86
  4934.9 2091.36  5048.6 2092.06  5054.1 2093.02  5071.8 2093.39  5077.3 2094.88
  5094.9 2095.58  5100.4 2097.24  5118.1 2097.98  5121.9 2099.08  5123.5 2099.54
  5152.2 2100.20  5182.3 2100.35  5229.1 2100.78  5260.7 2101.66  5270.4 2102.65
#Mann=7,-1,0
  4745.1    0.07       0  4765.4   0.035       0  4930.9   0.035       0
  4934.9   0.035       0  5121.9    0.07       0  5182.3   0.035       0
  5229.1    0.07       0
Bank Sta=4930.9,4934.9
Exp/Cntr=0.3,0.1

Type RM Length L Ch R = 1,147,0,0,0
BEGIN DESCRIPTION:
Sweetwater Creek Trib 27 T8_4 4507
END DESCRIPTION:
XS GIS Cut Line= 3
      1378846.56      6865921.94      1378675.13      6865638.20
      1378129.71      6865544.55
#Sta/Elev= 30
  4668.5 2106.13  4722.8 2105.17  4738.3 2106.90  4753.8 2107.48  4759.6 2104.31
  4775.1 2105.16  4781.0 2103.60  4833.4 2102.56  4854.7 2101.45  4891.6 2099.10
  4912.9 2095.94  4918.8 2094.24  4934.3 2092.64  4976.7 2090.97  5010.3 2090.77
  5026.1 2089.68  5026.4 2089.18  5030.1 2089.68  5050.7 2090.68  5088.1 2091.43
  5093.2 2092.53  5148.1 2094.24  5153.2 2095.78  5203.0 2096.27  5208.1 2097.49
  5213.2 2097.68  5456.7 2098.52  5487.1 2100.00  5537.9 2104.37  5553.4 2104.57
#Mann=6,-1,0
  4668.5   0.035       0  4976.7    0.07       0  5026.1    0.07       0
  5030.1    0.07       0  5050.7   0.035       0  5487.1    0.07       0
Bank Sta=5026.1,5030.1
Exp/Cntr=0.3,0.1

Chan Stop Cuts=-1