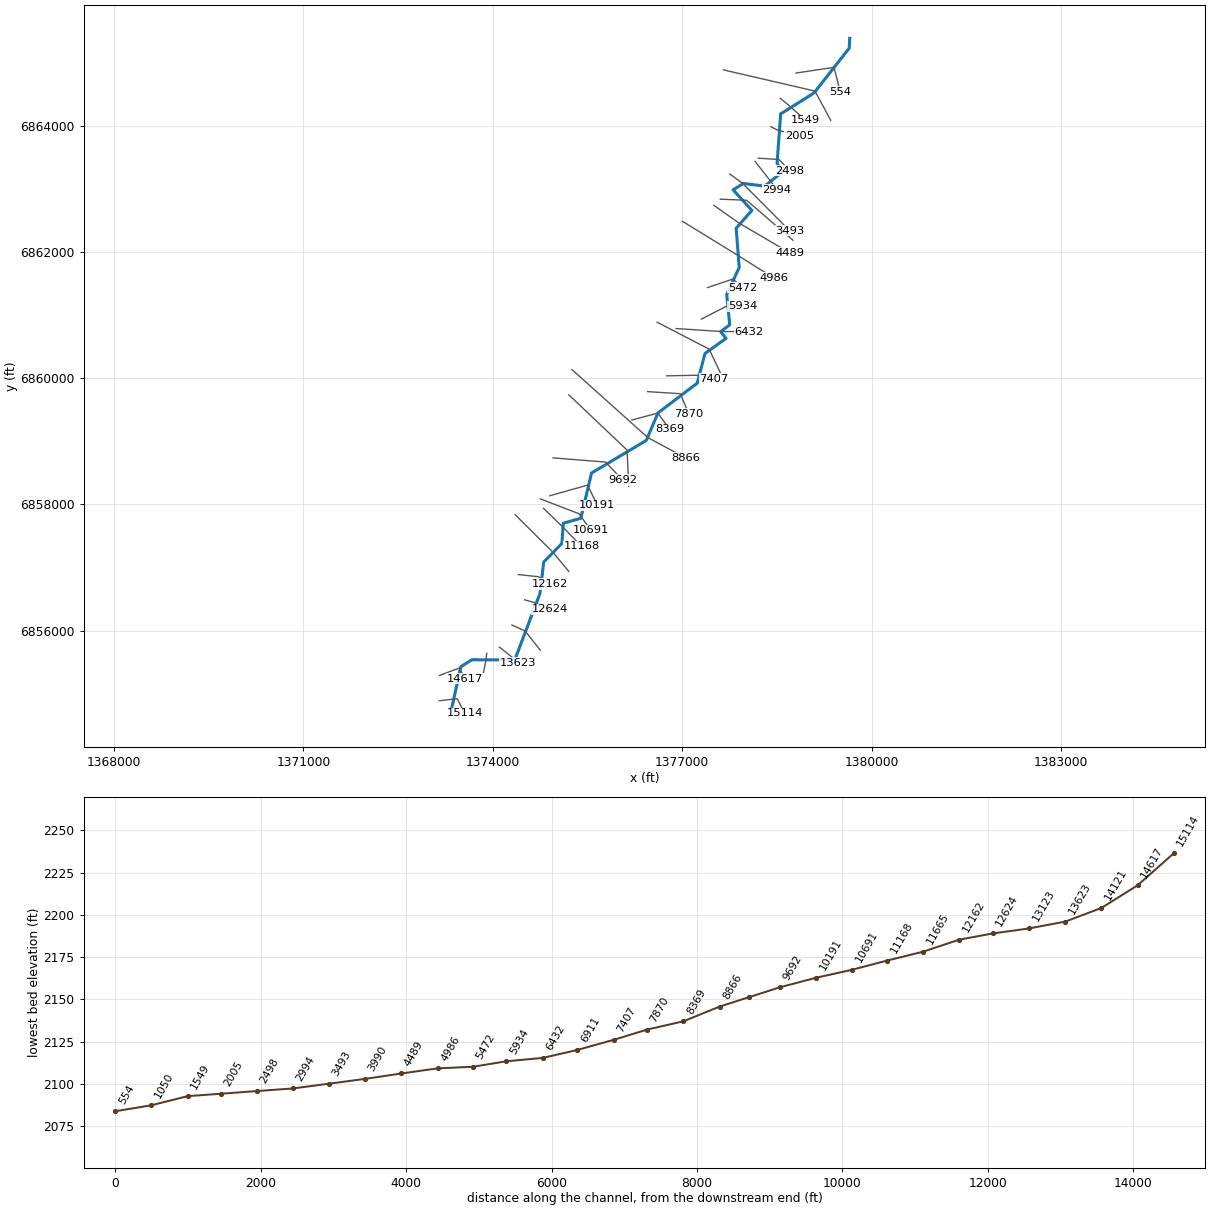
--- Sweetwater Creek Trib 27 T8_5.prj (project) ---

Proj Title=Sweetwater Creek Trib 27 T8_5 Base Level Engineering
Current Plan=p01
Default Exp/Contr=0.3,0.1
English Units
Geom File=g01
Flow File=f01
Plan File=p01
BEGIN DESCRIPTION:
Sweetwater Creek Trib 27 T8_5
END DESCRIPTION:

--- Sweetwater Creek Trib 27 T8_5.p01 (plan) ---

Plan Title=Multiple Run
Short Identifier=Multiple
Geom File=g01
Flow File=f01
Subcritical Flow
K Sum by GR= 0
Std Step Tol= 0.01
Critical Tol= 0.01
Num of Std Step Trials= 20
Max Error Tol= 0.3
Flow Tol Ratio= 0.001
Split Flow NTrial= 30
Split Flow Tol= 0.02
Split Flow Ratio= 0.02
Log Output Level= 0
Friction Slope Method= 1
Unsteady Friction Slope Method= 2
Unsteady Bridges Friction Slope Method= 1
Parabolic Critical Depth
Global Vel Dist=  1 , 1 , 1
Global Log Level= 0
CheckData=True
Encroach Param= -1, 0, 0, 0
BEGIN DESCRIPTION:
Multiple Run
END DESCRIPTION:

--- Sweetwater Creek Trib 27 T8_5.f01 (steady flow) ---

Flow Title=Multiple
Number of Profiles=7
Profile Names=10-year,25-year,50-year,1pct_min,100-year,1pct_plu,500-year
River Rch & RM= Sweetwater Creek,Reach-1,15114
     274     391     489     305     608    1213     952
River Rch & RM= Sweetwater Creek,Reach-1,6432
     398     577     730     459     917    1829    1464
Boundary for River Rch & Prof#=Sweetwater Creek,Reach-1,1
Up Type=0
Dn Type=3
Dn Slope=0.005
Boundary for River Rch & Prof#=Sweetwater Creek,Reach-1,2
Up Type=0
Dn Type=3
Dn Slope=0.005
Boundary for River Rch & Prof#=Sweetwater Creek,Reach-1,3
Up Type=0
Dn Type=3
Dn Slope=0.005
Boundary for River Rch & Prof#=Sweetwater Creek,Reach-1,4
Up Type=0
Dn Type=3
Dn Slope=0.005
Boundary for River Rch & Prof#=Sweetwater Creek,Reach-1,5
Up Type=0
Dn Type=3
Dn Slope=0.005
Boundary for River Rch & Prof#=Sweetwater Creek,Reach-1,6
Up Type=0
Dn Type=3
Dn Slope=0.005
Boundary for River Rch & Prof#=Sweetwater Creek,Reach-1,7
Up Type=0
Dn Type=3
Dn Slope=0.005

--- Sweetwater Creek Trib 27 T8_5.g01 (geometry) ---

Geom Title=Existing Conditions

River Reach=Sweetwater Creek,Reach-1
Reach XY= 30
      1373355.00      6854788.00      1373494.94      6855427.38
      1373670.22      6855537.75      1374349.60      6855535.29
      1374747.19      6856584.59      1374808.46      6857086.75
      1375095.85      6857381.27      1375118.23      6857701.81
      1375395.82      6857781.04      1375565.63      6858498.00
      1376432.29      6859014.10      1376618.50      6859451.68
      1377238.57      6859921.23      1377363.13      6860394.07
      1377696.03      6860631.33      1377612.01      6860738.21
      1377754.46      6860848.47      1377706.38      6861328.34
      1377904.82      6861756.27      1377856.36      6862378.35
      1378105.43      6862660.63      1377808.01      6862986.57
      1377970.21      6863087.49      1378308.67      6863045.69
      1378591.73      6863274.31      1378504.61      6863408.13
      1378560.83      6864190.30      1379088.36      6864521.29
      1379647.21      6865231.80      1379655.00      6865388.00

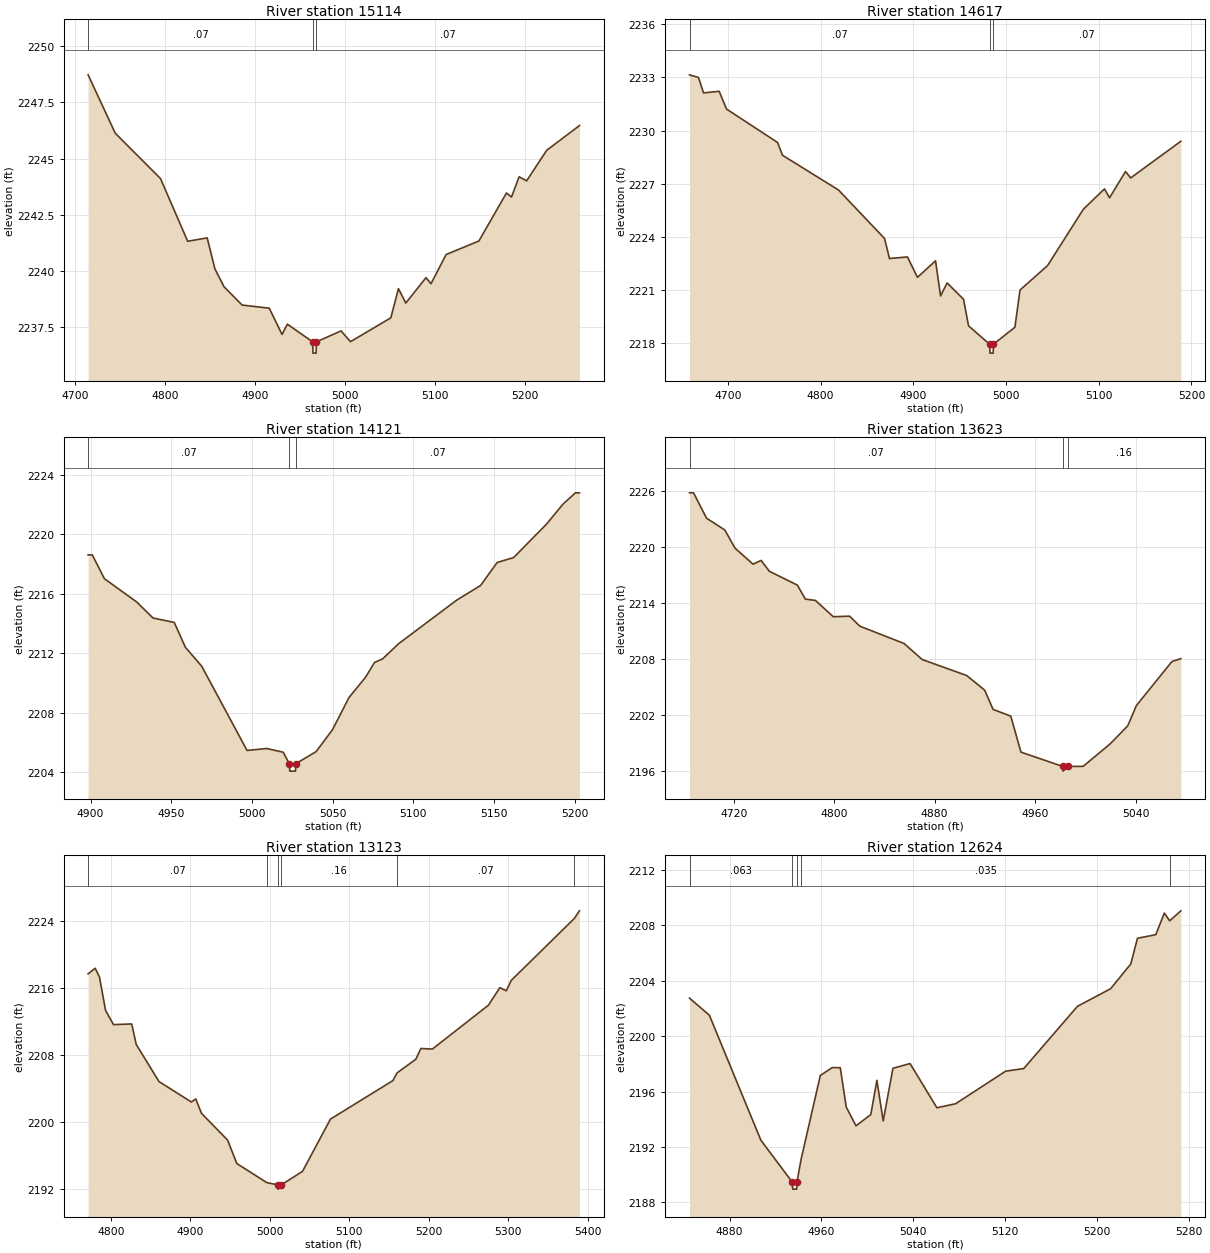
Type RM Length L Ch R = 1,15114,497,497,497
BEGIN DESCRIPTION:
Sweetwater Creek Trib 27 T8_5 30.0
END DESCRIPTION:
XS GIS Cut Line= 3
      1373155.01      6854888.00      1373438.56      6854921.24
      1373555.01      6854687.99
#Sta/Elev= 30
  4714.5 2248.73  4744.7 2246.13  4795.0 2244.11  4825.2 2241.32  4846.9 2241.47
  4855.5 2240.09  4865.5 2239.30  4885.7 2238.48  4915.9 2238.34  4930.1 2237.17
  4936.0 2237.63  4964.2 2236.84  4964.5 2236.34  4968.0 2236.34  4968.2 2236.84
  4995.7 2237.33  5006.2 2236.85  5051.0 2237.91  5059.5 2239.21  5067.7 2238.57
  5090.1 2239.70  5095.7 2239.43  5112.5 2240.73  5148.9 2241.33  5179.6 2243.47
  5185.2 2243.29  5193.6 2244.19  5202.0 2244.01  5224.3 2245.37  5260.7 2246.47
#Mann=3,-1,0
  4714.5    0.07       0  4964.2    0.07       0  4968.2    0.07       0
Bank Sta=4964.2,4968.2
Exp/Cntr=0.3,0.1

Type RM Length L Ch R = 1,14617,496,496,496
BEGIN DESCRIPTION:
Sweetwater Creek Trib 27 T8_5 29.0
END DESCRIPTION:
XS GIS Cut Line= 3
      1373155.03      6855288.01      1373474.44      6855408.55
      1373554.99      6855238.01
#Sta/Elev= 30
  4658.6 2233.15  4668.3 2233.00  4673.7 2232.13  4690.6 2232.22  4698.5 2231.22
  4753.6 2229.33  4758.9 2228.61  4819.3 2226.65  4869.0 2223.91  4874.3 2222.78
  4893.7 2222.87  4904.5 2221.72  4924.0 2222.65  4929.4 2220.67  4936.5 2221.40
  4954.2 2220.48  4959.6 2218.98  4982.4 2217.94  4982.7 2217.44  4986.2 2217.44
  4986.4 2217.94  5009.6 2218.90  5015.1 2221.00  5044.8 2222.38  5083.4 2225.56
  5106.2 2226.71  5111.7 2226.21  5128.9 2227.69  5134.5 2227.33  5188.6 2229.40
#Mann=3,-1,0
  4658.6    0.07       0  4982.4    0.07       0  4986.4    0.07       0
Bank Sta=4982.4,4986.4
Exp/Cntr=0.3,0.1

Type RM Length L Ch R = 1,14121,498,498,498
BEGIN DESCRIPTION:
Sweetwater Creek Trib 27 T8_5 28.0
END DESCRIPTION:
XS GIS Cut Line= 3
      1373905.00      6855638.04      1373895.13      6855537.02
      1373855.01      6855338.03
#Sta/Elev= 30
  4898.5 2218.61  4901.1 2218.61  4908.6 2217.01  4928.7 2215.44  4938.7 2214.37
  4951.9 2214.07  4958.8 2212.40  4968.9 2211.13  4997.0 2205.47  5009.2 2205.60
  5019.4 2205.35  5023.2 2204.58  5023.5 2204.08  5027.0 2204.08  5027.2 2204.58
  5039.8 2205.39  5050.0 2206.87  5060.2 2209.03  5070.4 2210.38  5076.0 2211.38
  5081.1 2211.63  5090.8 2212.63  5126.8 2215.56  5141.8 2216.56  5152.0 2218.10
  5162.2 2218.43  5182.7 2220.69  5192.8 2222.02  5200.5 2222.78  5203.0 2222.78
#Mann=3,-1,0
  4898.5    0.07       0  5023.2    0.07       0  5027.2    0.07       0
Bank Sta=5023.2,5027.2
Exp/Cntr=0.3,0.1

Type RM Length L Ch R = 1,13623,500,500,500
BEGIN DESCRIPTION:
Sweetwater Creek Trib 27 T8_5 27.0
END DESCRIPTION:
XS GIS Cut Line= 3
      1374104.98      6855738.01      1374352.83      6855543.27
      1374404.99      6855488.01
#Sta/Elev= 30
  4684.8 2225.76  4688.0 2225.76  4698.4 2223.04  4712.9 2221.79  4721.0 2219.85
  4735.4 2218.13  4741.8 2218.53  4748.4 2217.37  4770.7 2215.89  4777.0 2214.40
  4785.1 2214.25  4799.3 2212.51  4812.3 2212.57  4820.4 2211.50  4855.6 2209.65
  4870.1 2207.93  4905.4 2206.23  4919.8 2204.66  4926.5 2202.60  4940.6 2201.88
  4948.7 2198.03  4982.0 2196.50  4982.2 2196.00  4986.0 2196.50  4998.2 2196.51
  5019.6 2198.90  5033.7 2200.84  5040.6 2203.01  5068.9 2207.72  5076.0 2208.03
#Mann=3,-1,0
  4684.8    0.07       0  4982.0    0.07       0  4986.0    0.16       0
Bank Sta=4982,4986
Exp/Cntr=0.3,0.1

Type RM Length L Ch R = 1,13123,499,499,499
BEGIN DESCRIPTION:
Sweetwater Creek Trib 27 T8_5 26.0
END DESCRIPTION:
XS GIS Cut Line= 3
      1374304.97      6856088.01      1374513.43      6855993.94
      1374754.99      6855688.01
#Sta/Elev= 30
  4771.3 2217.67  4780.2 2218.34  4785.6 2217.29  4793.3 2213.29  4803.3 2211.60
  4826.2 2211.68  4831.9 2209.23  4860.5 2204.80  4901.3 2202.35  4906.8 2202.72
  4914.0 2201.00  4946.9 2197.80  4958.5 2195.00  4996.2 2192.72  5010.3 2192.44
  5010.5 2191.94  5014.3 2192.44  5041.2 2194.06  5076.4 2200.31  5155.0 2204.91
  5160.1 2205.82  5183.8 2207.46  5190.2 2208.75  5204.7 2208.68  5275.2 2213.92
  5289.6 2216.02  5297.7 2215.64  5304.0 2216.89  5383.2 2224.27  5389.8 2225.20
#Mann=6,-1,0
  4771.3    0.07       0  4996.2    0.16       0  5010.3    0.07       0
  5014.3    0.16       0  5160.1    0.07       0  5383.2   0.063       0
Bank Sta=5010.3,5014.3
Exp/Cntr=0.3,0.1

Type RM Length L Ch R = 1,12624,462,462,462
BEGIN DESCRIPTION:
Sweetwater Creek Trib 27 T8_5 25.0
END DESCRIPTION:
XS GIS Cut Line= 3
      1374505.00      6856488.00      1374654.56      6856447.28
      1374904.96      6856338.02
#Sta/Elev= 30
  4845.0 2202.74  4862.3 2201.51  4907.2 2192.49  4934.6 2189.46  4934.9 2188.96
  4938.4 2188.96  4938.6 2189.46  4942.3 2191.13  4959.0 2197.16  4969.4 2197.73
  4976.4 2197.72  4981.6 2194.88  4990.1 2193.53  5003.0 2194.34  5008.3 2196.81
  5013.8 2193.88  5022.3 2197.68  5037.2 2198.02  5060.6 2194.83  5076.9 2195.12
  5120.5 2197.47  5136.3 2197.66  5183.1 2202.15  5212.0 2203.42  5229.6 2205.21
  5235.4 2207.06  5251.4 2207.32  5258.8 2208.88  5263.5 2208.32  5273.2 2209.04
#Mann=5,-1,0
  4845.0   0.063       0  4934.6   0.035       0  4938.6   0.063       0
  4942.3   0.035       0  5263.5   0.094       0
Bank Sta=4934.6,4938.6
Exp/Cntr=0.3,0.1

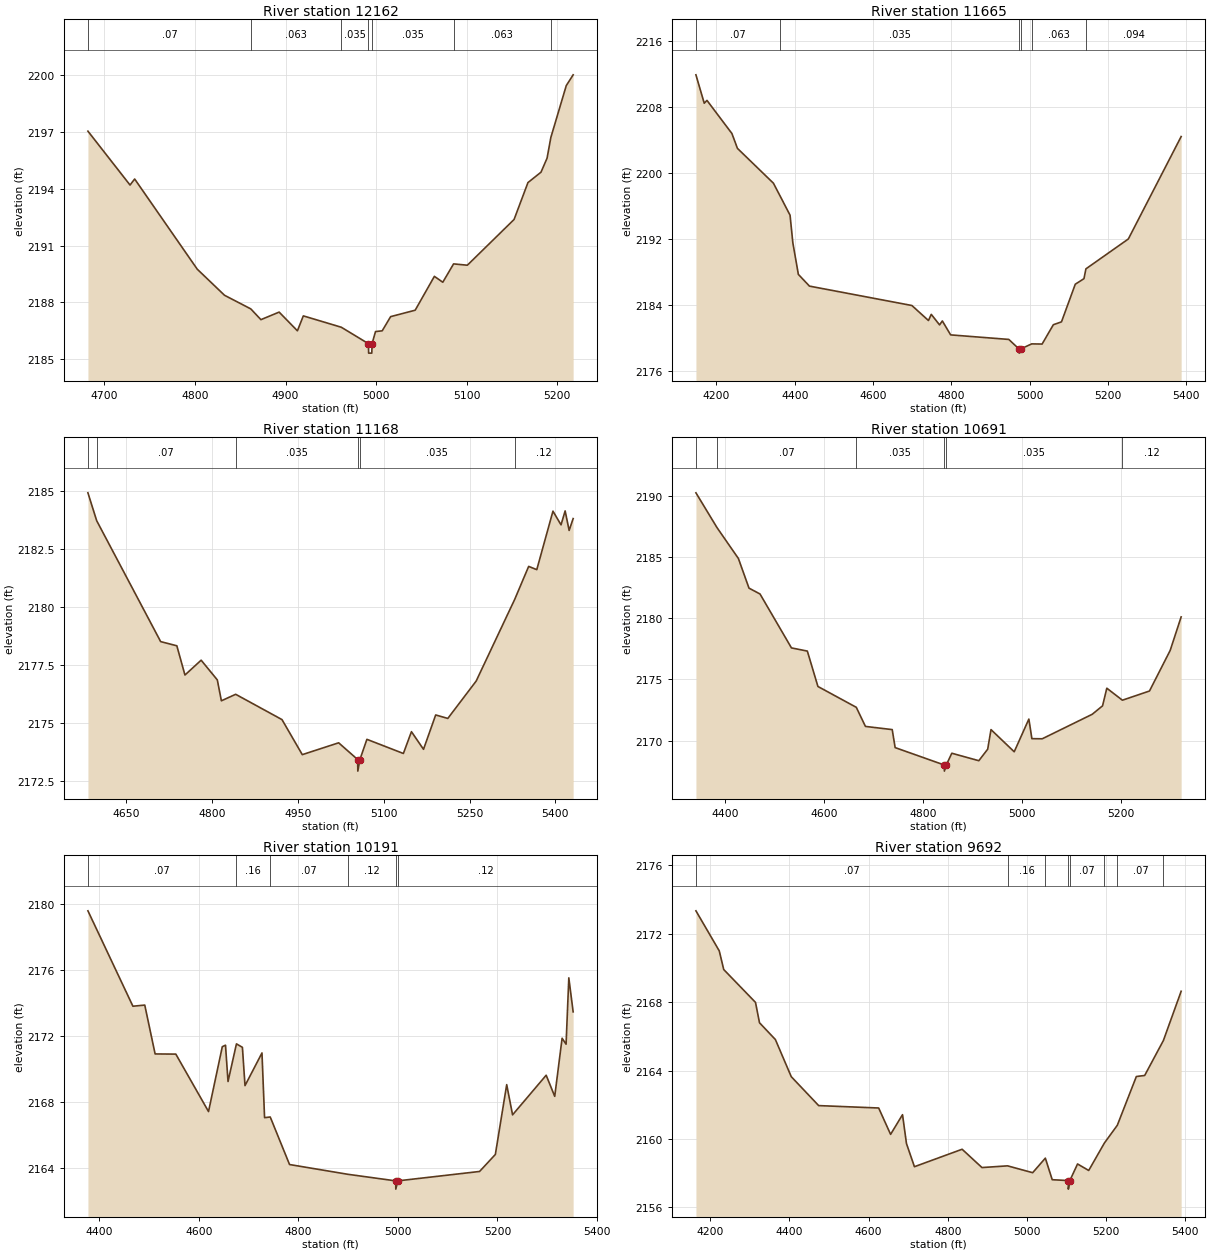
Type RM Length L Ch R = 1,12162,497,497,497
BEGIN DESCRIPTION:
Sweetwater Creek Trib 27 T8_5 24.0
END DESCRIPTION:
XS GIS Cut Line= 3
      1374405.01      6856888.00      1374721.47      6856854.75
      1374904.98      6856738.01
#Sta/Elev= 30
  4681.8 2197.05  4728.3 2194.20  4733.4 2194.52  4802.5 2189.75  4832.6 2188.37
  4861.6 2187.65  4872.8 2187.08  4892.9 2187.48  4913.1 2186.49  4919.6 2187.28
  4961.5 2186.68  4991.5 2185.81  4991.7 2185.31  4995.2 2185.31  4995.5 2185.81
  4999.3 2186.45  5006.7 2186.49  5016.0 2187.24  5043.1 2187.58  5064.3 2189.37
  5073.6 2189.06  5085.5 2190.03  5100.7 2189.96  5152.3 2192.38  5167.6 2194.33
  5182.0 2194.88  5188.7 2195.62  5192.9 2196.72  5209.9 2199.46  5217.5 2200.03
#Mann=7,-1,0
  4681.8    0.07       0  4861.6   0.063       0  4961.5   0.035       0
  4991.5   0.035       0  4995.5   0.035       0  5085.5   0.063       0
  5192.9   0.094       0
Bank Sta=4991.5,4995.5
Exp/Cntr=0.3,0.1

Type RM Length L Ch R = 1,11665,497,497,497
BEGIN DESCRIPTION:
Sweetwater Creek Trib 27 T8_5 23.0
END DESCRIPTION:
XS GIS Cut Line= 3
      1374355.02      6857837.98      1374958.99      6857236.32
      1375205.01      6856937.98
#Sta/Elev= 30
  4147.5 2211.88  4168.7 2208.44  4175.7 2208.78  4239.4 2204.77  4253.5 2202.97
  4345.4 2198.75  4362.9 2197.16  4387.9 2194.87  4395.0 2191.53  4409.1 2187.70
  4437.4 2186.28  4699.0 2183.93  4741.4 2182.11  4748.5 2182.86  4769.7 2181.58
  4776.8 2182.06  4798.0 2180.37  4946.5 2179.82  4972.8 2178.66  4973.0 2178.16
  4976.8 2178.66  5005.0 2179.28  5031.6 2179.26  5060.3 2181.60  5081.1 2181.95
  5116.3 2186.51  5138.5 2187.18  5143.5 2188.37  5251.8 2191.99  5386.7 2204.40
#Mann=6,-1,0
  4147.5    0.07       0  4362.9   0.035       0  4972.8   0.035       0
  4976.8   0.035       0  5005.0   0.063       0  5143.5   0.094       0
Bank Sta=4972.8,4976.8
Exp/Cntr=0.3,0.1

Type RM Length L Ch R = 1,11168,477,477,477
BEGIN DESCRIPTION:
Sweetwater Creek Trib 27 T8_5 22.0
END DESCRIPTION:
XS GIS Cut Line= 3
      1374804.99      6857938.01      1375104.54      6857647.33
      1375404.98      6857338.02
#Sta/Elev= 30
  4582.6 2184.90  4597.9 2183.70  4709.8 2178.49  4738.1 2178.31  4752.3 2177.05
  4780.6 2177.69  4808.9 2176.84  4816.0 2175.94  4841.0 2176.22  4922.0 2175.13
  4957.5 2173.62  5021.1 2174.13  5054.3 2173.41  5054.6 2172.91  5058.3 2173.41
  5070.5 2174.28  5134.3 2173.67  5148.4 2174.61  5169.5 2173.85  5190.8 2175.33
  5212.0 2175.18  5261.6 2176.79  5329.0 2180.31  5353.4 2181.73  5367.6 2181.59
  5395.9 2184.11  5410.0 2183.52  5417.2 2184.12  5424.2 2183.28  5431.2 2183.79
#Mann=6,-1,0
  4582.6   0.035       0  4597.9    0.07       0  4841.0   0.035       0
  5054.3   0.035       0  5058.3   0.035       0  5329.0    0.12       0
Bank Sta=5054.3,5058.3
Exp/Cntr=0.3,0.1

Type RM Length L Ch R = 1,10691,500,500,500
BEGIN DESCRIPTION:
Sweetwater Creek Trib 27 T8_5 21.0
END DESCRIPTION:
XS GIS Cut Line= 3
      1374754.97      6858088.01      1375369.07      6857851.15
      1375555.00      6857588.01
#Sta/Elev= 30
  4341.8 2190.23  4384.4 2187.39  4427.6 2184.87  4449.0 2182.45  4471.3 2181.97
  4534.8 2177.57  4566.9 2177.31  4588.3 2174.42  4665.8 2172.72  4684.3 2171.16
  4738.4 2170.90  4744.3 2169.43  4843.6 2168.01  4843.8 2167.51  4847.6 2168.01
  4858.8 2168.97  4913.4 2168.36  4931.3 2169.30  4938.0 2170.90  4984.9 2169.09
  5014.5 2171.76  5020.6 2170.16  5041.5 2170.15  5142.5 2172.15  5163.4 2172.84
  5172.0 2174.28  5203.5 2173.30  5258.2 2174.05  5300.0 2177.36  5322.2 2180.10
#Mann=6,-1,0
  4341.8   0.035       0  4384.4    0.07       0  4665.8   0.035       0
  4843.6   0.035       0  4847.6   0.035       0  5203.5    0.12       0
Bank Sta=4843.6,4847.6
Exp/Cntr=0.3,0.1

Type RM Length L Ch R = 1,10191,499,499,499
BEGIN DESCRIPTION:
Sweetwater Creek Trib 27 T8_5 20.0
END DESCRIPTION:
XS GIS Cut Line= 3
      1374905.01      6858138.00      1375504.63      6858306.33
      1375655.02      6857987.97
#Sta/Elev= 30
  4377.2 2179.59  4467.6 2173.81  4491.4 2173.88  4512.2 2170.92  4553.8 2170.91
  4619.5 2167.43  4647.2 2171.36  4653.6 2171.45  4658.7 2169.25  4675.6 2171.53
  4687.6 2171.32  4692.8 2169.00  4726.9 2170.98  4732.1 2167.06  4743.5 2167.10
  4782.3 2164.22  4899.1 2163.63  4995.6 2163.23  4995.8 2162.73  4999.6 2163.23
  5164.1 2163.80  5195.8 2164.83  5218.6 2169.06  5230.4 2167.23  5297.9 2169.63
  5315.1 2168.35  5329.9 2171.87  5337.9 2171.51  5343.4 2175.53  5352.1 2173.47
#Mann=6,-1,0
  4377.2    0.07       0  4675.6    0.16       0  4743.5    0.07       0
  4899.1    0.12       0  4995.6    0.07       0  4999.6    0.12       0
Bank Sta=4995.6,4999.6
Exp/Cntr=0.3,0.1

Type RM Length L Ch R = 1,9692,415,415,415
BEGIN DESCRIPTION:
Sweetwater Creek Trib 27 T8_5 19.0
END DESCRIPTION:
XS GIS Cut Line= 3
      1374955.05      6858738.00      1375788.29      6858671.43
      1376055.01      6858387.99
#Sta/Elev= 30
  4164.1 2173.33  4223.0 2170.99  4234.3 2169.90  4314.5 2167.98  4324.6 2166.79
  4364.7 2165.81  4404.8 2163.64  4474.0 2161.95  4625.5 2161.81  4655.6 2160.27
  4685.7 2161.42  4695.7 2159.73  4715.8 2158.38  4836.2 2159.40  4886.3 2158.33
  4950.9 2158.43  5014.3 2158.03  5046.3 2158.88  5063.7 2157.62  5104.2 2157.57
  5104.4 2157.07  5108.2 2157.57  5127.6 2158.54  5155.8 2158.16  5195.3 2159.76
  5228.0 2160.80  5276.1 2163.65  5297.1 2163.71  5344.3 2165.75  5389.2 2168.63
#Mann=8,-1,0
  4164.1    0.07       0  4950.9    0.16       0  5046.3    0.07       0
  5104.2    0.07       0  5108.2    0.07       0  5195.3    0.16       0
  5228.0    0.07       0  5344.3   0.063       0
Bank Sta=5104.2,5108.2
Exp/Cntr=0.3,0.1

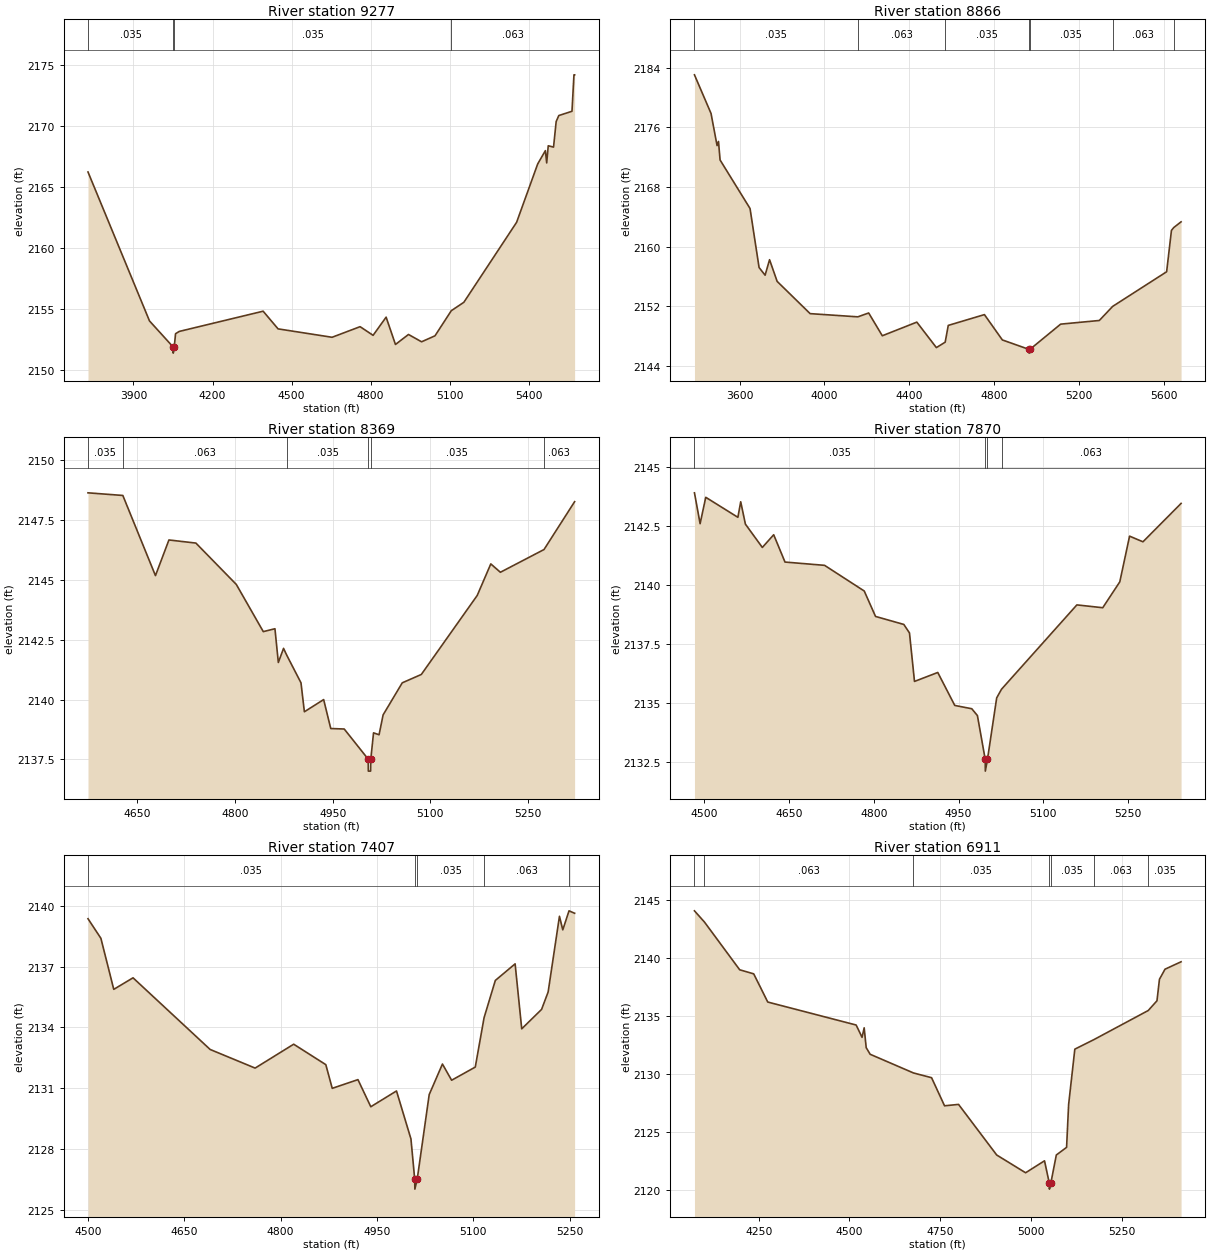
Type RM Length L Ch R = 1,9277,411,411,411
BEGIN DESCRIPTION:
Sweetwater Creek Trib 27 T8_5 18.0
END DESCRIPTION:
XS GIS Cut Line= 3
      1375205.03      6859737.97      1376128.13      6858861.82
      1376155.00      6858288.05
#Sta/Elev= 30
  3727.3 2166.21  3960.8 2153.99  4050.7 2151.85  4050.9 2151.35  4054.7 2151.85
  4059.6 2152.94  4073.7 2153.13  4392.1 2154.79  4448.7 2153.34  4653.8 2152.65
  4760.1 2153.52  4809.5 2152.81  4858.9 2154.30  4894.4 2152.06  4943.8 2152.88
  4993.5 2152.28  5044.4 2152.77  5106.3 2154.83  5154.0 2155.52  5354.2 2162.08
  5434.3 2166.87  5463.4 2167.96  5468.4 2166.95  5474.3 2168.36  5494.4 2168.25
  5504.4 2170.35  5514.4 2170.84  5564.4 2171.19  5571.9 2174.18  5574.4 2174.18
#Mann=4,-1,0
  3727.3   0.035       0  4050.7   0.035       0  4054.7   0.035       0
  5106.3   0.063       0
Bank Sta=4050.7,4054.7
Exp/Cntr=0.3,0.1

Type RM Length L Ch R = 1,8866,497,497,497
BEGIN DESCRIPTION:
Sweetwater Creek Trib 27 T8_5 17.0
END DESCRIPTION:
XS GIS Cut Line= 3
      1375254.98      6860138.01      1376455.21      6859060.56
      1377054.98      6858738.01
#Sta/Elev= 30
  3387.1 2183.05  3465.2 2177.87  3493.7 2173.55  3500.4 2174.11  3507.9 2171.62
  3649.1 2165.11  3691.7 2157.19  3720.1 2156.16  3741.1 2158.24  3776.8 2155.33
  3932.4 2151.00  4157.3 2150.57  4208.3 2151.09  4272.6 2148.03  4435.3 2149.86
  4527.5 2146.44  4569.0 2147.17  4583.5 2149.42  4754.0 2150.87  4838.5 2147.47
  4964.3 2146.20  4964.5 2145.70  4968.3 2146.20  5113.3 2149.59  5295.5 2150.08
  5358.4 2151.97  5612.9 2156.62  5635.6 2162.17  5646.3 2162.55  5681.0 2163.32
#Mann=7,-1,0
  3387.1   0.035       0  4157.3   0.063       0  4569.0   0.035       0
  4964.3   0.035       0  4968.3   0.035       0  5358.4   0.063       0
  5646.3   0.035       0
Bank Sta=4964.3,4968.3
Exp/Cntr=0.3,0.1

Type RM Length L Ch R = 1,8369,499,499,499
BEGIN DESCRIPTION:
Sweetwater Creek Trib 27 T8_5 16.0
END DESCRIPTION:
XS GIS Cut Line= 3
      1376204.95      6859337.99      1376616.11      6859448.32
      1376804.98      6859188.03
#Sta/Elev= 30
  4574.3 2148.64  4627.8 2148.53  4677.9 2145.18  4698.6 2146.67  4740.0 2146.54
  4802.1 2144.81  4843.5 2142.84  4861.4 2142.96  4866.6 2141.55  4874.6 2142.14
  4879.8 2141.84  4901.4 2140.70  4906.6 2139.49  4936.2 2140.00  4947.1 2138.79
  4967.8 2138.77  5004.6 2137.51  5004.8 2137.01  5008.3 2137.01  5008.6 2137.51
  5012.8 2138.61  5021.3 2138.53  5027.5 2139.36  5056.9 2140.70  5086.2 2141.05
  5172.0 2144.35  5192.9 2145.67  5207.6 2145.32  5274.6 2146.27  5321.6 2148.27
#Mann=6,-1,0
  4574.3   0.035       0  4627.8   0.063       0  4879.8   0.035       0
  5004.6   0.035       0  5008.6   0.035       0  5274.6   0.063       0
Bank Sta=5004.6,5008.6
Exp/Cntr=0.3,0.1

Type RM Length L Ch R = 1,7870,463,463,463
BEGIN DESCRIPTION:
Sweetwater Creek Trib 27 T8_5 15.0
END DESCRIPTION:
XS GIS Cut Line= 3
      1376455.03      6859788.00      1376971.48      6859755.12
      1377105.01      6859437.98
#Sta/Elev= 30
  4482.5 2143.92  4492.5 2142.61  4502.5 2143.73  4559.4 2142.88  4564.4 2143.54
  4572.7 2142.59  4602.7 2141.60  4622.8 2142.14  4642.8 2140.98  4712.9 2140.84
  4783.1 2139.75  4803.1 2138.67  4853.2 2138.33  4863.2 2137.97  4872.1 2135.91
  4913.3 2136.29  4943.4 2134.89  4973.5 2134.75  4983.5 2134.46  4997.3 2132.60
  4997.5 2132.10  5001.3 2132.60  5017.6 2135.21  5026.2 2135.58  5159.6 2139.16
  5205.4 2139.04  5235.6 2140.14  5252.9 2142.08  5276.6 2141.84  5344.1 2143.47
#Mann=4,-1,0
  4482.5   0.035       0  4997.3   0.035       0  5001.3   0.035       0
  5026.2   0.063       0
Bank Sta=4997.3,5001.3
Exp/Cntr=0.3,0.1

Type RM Length L Ch R = 1,7407,496,496,496
BEGIN DESCRIPTION:
Sweetwater Creek Trib 27 T8_5 14.0
END DESCRIPTION:
XS GIS Cut Line= 3
      1376754.95      6860038.00      1377254.65      6860048.19
      1377505.01      6859988.00
#Sta/Elev= 30
  4500.2 2139.37  4520.3 2138.40  4540.3 2135.88  4570.3 2136.45  4690.3 2132.91
  4760.3 2131.99  4820.3 2133.17  4870.3 2132.16  4880.3 2130.99  4920.3 2131.42
  4940.3 2130.08  4980.3 2130.86  5002.8 2128.49  5008.6 2126.51  5008.9 2126.01
  5012.6 2126.51  5031.2 2130.68  5051.8 2132.19  5066.1 2131.39  5102.9 2132.04
  5116.6 2134.48  5134.1 2136.32  5164.9 2137.14  5175.2 2133.93  5206.1 2134.89
  5216.3 2135.75  5233.9 2139.49  5239.1 2138.82  5248.8 2139.76  5257.5 2139.64
#Mann=5,-1,0
  4500.2   0.035       0  5008.6   0.035       0  5012.6   0.035       0
  5116.6   0.063       0  5248.8   0.035       0
Bank Sta=5008.6,5012.6
Exp/Cntr=0.3,0.1

Type RM Length L Ch R = 1,6911,479,479,479
BEGIN DESCRIPTION:
Sweetwater Creek Trib 27 T8_5 13.0
END DESCRIPTION:
XS GIS Cut Line= 3
      1376604.96      6860888.02      1377428.07      6860461.85
      1377605.00      6860088.00
#Sta/Elev= 30
  4073.1 2144.04  4100.7 2143.07  4197.7 2138.96  4236.3 2138.61  4275.0 2136.18
  4518.5 2134.20  4534.8 2133.14  4540.6 2133.96  4546.2 2132.25  4557.1 2131.68
  4676.4 2130.07  4726.3 2129.66  4762.0 2127.24  4800.6 2127.36  4905.7 2123.00
  4985.3 2121.47  5037.4 2122.50  5050.7 2120.56  5050.9 2120.06  5054.7 2120.56
  5069.9 2123.00  5098.2 2123.66  5103.8 2127.35  5120.9 2132.12  5173.3 2132.94
  5323.1 2135.45  5347.2 2136.29  5354.0 2138.14  5369.3 2139.01  5413.6 2139.65
#Mann=7,-1,0
  4073.1   0.035       0  4100.7   0.063       0  4676.4   0.035       0
  5050.7   0.035       0  5054.7   0.035       0  5173.3   0.063       0
  5323.1   0.035       0
Bank Sta=5050.7,5054.7
Exp/Cntr=0.3,0.1

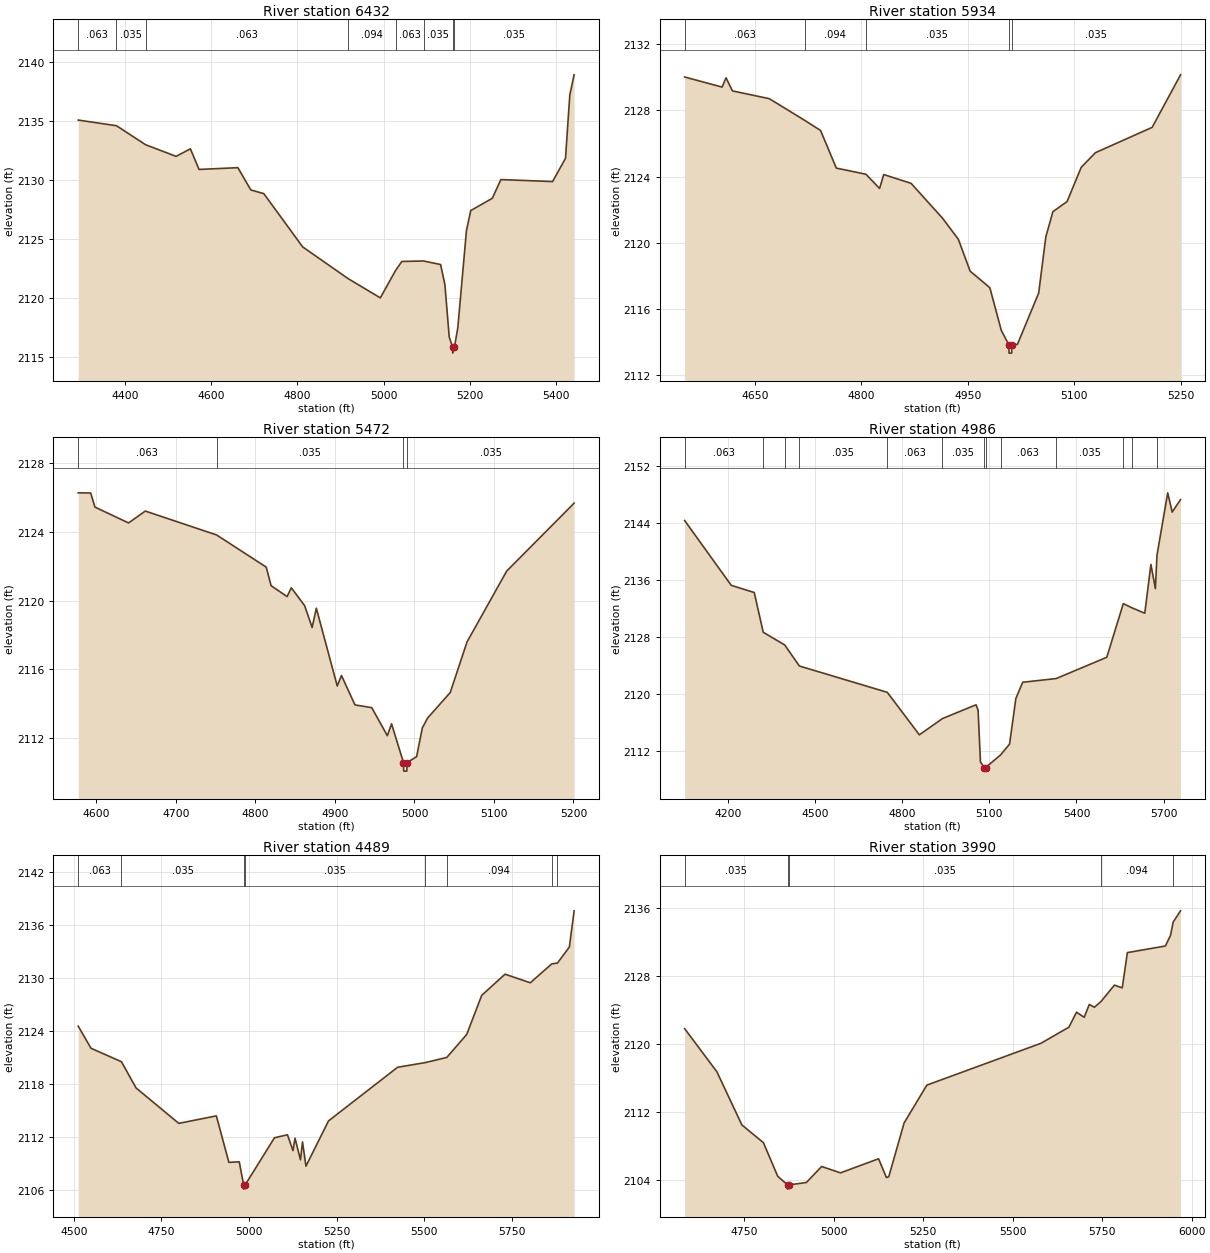
Type RM Length L Ch R = 1,6432,498,498,498
BEGIN DESCRIPTION:
Sweetwater Creek Trib 27 T8_5 12.0
END DESCRIPTION:
XS GIS Cut Line= 3
      1376905.03      6860788.00      1377612.50      6860741.58
      1378054.99      6860738.00
#Sta/Elev= 30
  4291.0 2135.11  4379.9 2134.63  4447.4 2133.02  4518.3 2132.03  4551.5 2132.67
  4571.6 2130.92  4661.8 2131.07  4691.8 2129.18  4721.9 2128.87  4812.1 2124.35
  4917.9 2121.65  4992.5 2120.02  5028.0 2122.35  5042.5 2123.11  5092.9 2123.15
  5132.5 2122.85  5142.5 2121.14  5152.5 2116.70  5160.5 2115.83  5160.7 2115.33
  5164.6 2115.83  5172.5 2117.50  5192.5 2125.73  5202.5 2127.43  5252.5 2128.47
  5272.5 2130.06  5392.5 2129.89  5422.5 2131.86  5432.5 2137.24  5442.5 2138.95
#Mann=8,-1,0
  4291.0   0.063       0  4379.9   0.035       0  4447.4   0.063       0
  4917.9   0.094       0  5028.0   0.063       0  5092.9   0.035       0
  5160.5    0.07       0  5164.6   0.035       0
Bank Sta=5160.5,5164.6
Exp/Cntr=0.3,0.1

Type RM Length L Ch R = 1,5934,462,462,462
BEGIN DESCRIPTION:
Sweetwater Creek Trib 27 T8_5 11.0
END DESCRIPTION:
XS GIS Cut Line= 3
      1377304.97      6860937.98      1377705.00      6861142.55
      1377954.96      6861138.00
#Sta/Elev= 30
  4550.7 2130.02  4603.5 2129.41  4609.1 2129.97  4618.1 2129.18  4670.1 2128.71
  4720.1 2127.40  4742.4 2126.79  4764.6 2124.52  4806.3 2124.15  4825.6 2123.29
  4831.5 2124.13  4870.0 2123.60  4914.5 2121.49  4936.7 2120.22  4953.3 2118.30
  4981.1 2117.30  4997.2 2114.73  5007.9 2113.85  5008.2 2113.35  5011.9 2113.35
  5012.2 2113.85  5020.0 2113.88  5050.0 2116.98  5060.0 2120.36  5070.0 2121.89
  5090.0 2122.50  5110.0 2124.57  5130.0 2125.45  5210.0 2126.98  5250.0 2130.15
#Mann=5,-1,0
  4550.7   0.063       0  4720.1   0.094       0  4806.3   0.035       0
  5007.9   0.035       0  5012.2   0.035       0
Bank Sta=5007.9,5012.2
Exp/Cntr=0.3,0.1

Type RM Length L Ch R = 1,5472,486,486,486
BEGIN DESCRIPTION:
Sweetwater Creek Trib 27 T8_5 10.0
END DESCRIPTION:
XS GIS Cut Line= 3
      1377405.03      6861438.01      1377805.94      6861572.61
      1377954.96      6861438.03
#Sta/Elev= 30
  4577.1 2126.27  4592.8 2126.26  4598.2 2125.44  4640.4 2124.52  4661.5 2125.21
  4751.2 2123.82  4813.6 2121.95  4819.7 2120.87  4839.8 2120.24  4845.1 2120.75
  4861.9 2119.71  4871.3 2118.44  4876.6 2119.56  4902.9 2115.04  4908.2 2115.65
  4925.2 2113.94  4946.3 2113.78  4965.9 2112.15  4971.2 2112.84  4986.2 2110.59
  4986.5 2110.09  4990.4 2110.09  4990.7 2110.59  5002.7 2110.93  5009.9 2112.60
  5016.6 2113.18  5045.0 2114.66  5066.1 2117.60  5116.0 2121.72  5200.8 2125.67
#Mann=4,-1,0
  4577.1   0.063       0  4751.2   0.035       0  4986.2   0.035       0
  4990.7   0.035       0
Bank Sta=4986.2,4990.7
Exp/Cntr=0.3,0.1

Type RM Length L Ch R = 1,4986,497,497,497
BEGIN DESCRIPTION:
Sweetwater Creek Trib 27 T8_5 9.0
END DESCRIPTION:
XS GIS Cut Line= 3
      1377005.00      6862488.00      1377812.88      6861991.22
      1378454.98      6861588.01
#Sta/Elev= 30
  4051.6 2144.30  4212.0 2135.21  4291.2 2134.20  4322.1 2128.63  4396.1 2126.85
  4446.4 2123.90  4749.0 2120.21  4859.4 2114.25  4938.9 2116.53  5054.4 2118.46
  5061.5 2117.71  5069.7 2110.44  5082.7 2109.66  5083.0 2109.16  5087.2 2109.66
  5138.8 2111.43  5169.8 2112.95  5191.4 2119.33  5215.0 2121.62  5330.1 2122.14
  5504.4 2125.12  5561.2 2132.64  5592.5 2132.03  5635.1 2131.30  5656.3 2138.14
  5671.6 2134.75  5677.2 2139.44  5714.1 2148.18  5729.4 2145.48  5758.2 2147.23
#Mann=13,-1,0
  4051.6   0.063       0  4322.1   0.035       0  4396.1   0.063       0
  4446.4   0.035       0  4749.0   0.063       0  4938.9   0.035       0
  5082.7   0.035       0  5087.2   0.035       0  5138.8   0.063       0
  5330.1   0.035       0  5561.2   0.063       0  5592.5   0.035       0
  5677.2   0.063       0
Bank Sta=5082.7,5087.2
Exp/Cntr=0.3,0.1

Type RM Length L Ch R = 1,4489,499,499,499
BEGIN DESCRIPTION:
Sweetwater Creek Trib 27 T8_5 8.0
END DESCRIPTION:
XS GIS Cut Line= 3
      1377505.02      6862737.99      1377904.49      6862458.21
      1378705.01      6861988.00
#Sta/Elev= 30
  4512.3 2124.58  4548.9 2122.08  4635.9 2120.55  4677.5 2117.59  4799.5 2113.58
  4906.8 2114.43  4942.5 2109.17  4972.2 2109.23  4984.6 2106.64  4984.9 2106.14
  4989.4 2106.64  5072.7 2111.95  5109.9 2112.29  5125.6 2110.50  5131.4 2111.90
  5147.0 2109.46  5152.8 2111.48  5162.7 2108.74  5227.1 2113.86  5424.4 2119.93
  5503.8 2120.46  5564.7 2121.04  5621.7 2123.64  5664.6 2128.07  5731.2 2130.46
  5803.3 2129.49  5864.7 2131.63  5880.8 2131.72  5914.8 2133.53  5928.4 2137.63
#Mann=8,-1,0
  4512.3   0.063       0  4635.9   0.035       0  4984.6   0.035       0
  4989.4   0.035       0  5503.8   0.063       0  5564.7   0.094       0
  5864.7   0.063       0  5880.8   0.094       0
Bank Sta=4984.6,4989.4
Exp/Cntr=0.3,0.1

Type RM Length L Ch R = 1,3990,497,497,497
BEGIN DESCRIPTION:
Sweetwater Creek Trib 27 T8_5 7.0
END DESCRIPTION:
XS GIS Cut Line= 3
      1377605.01      6862838.00      1378021.79      6862821.56
      1378754.99      6862188.01
#Sta/Elev= 30
  4582.9 2121.79  4673.0 2116.72  4743.0 2110.47  4803.1 2108.39  4843.1 2104.44
  4870.6 2103.43  4871.0 2102.93  4875.6 2103.43  4923.2 2103.71  4965.8 2105.59
  5018.6 2104.84  5125.0 2106.50  5146.9 2104.29  5153.5 2104.39  5196.3 2110.70
  5259.9 2115.15  5579.1 2120.07  5657.0 2121.96  5678.3 2123.72  5699.7 2123.12
  5714.0 2124.63  5728.2 2124.30  5746.6 2124.97  5784.2 2126.90  5806.1 2126.58
  5820.4 2130.72  5926.8 2131.50  5941.0 2132.75  5948.5 2134.32  5969.0 2135.63
#Mann=5,-1,0
  4582.9   0.035       0  4870.6   0.035       0  4875.6   0.035       0
  5746.6   0.094       0  5948.5   0.125       0
Bank Sta=4870.6,4875.6
Exp/Cntr=0.3,0.1

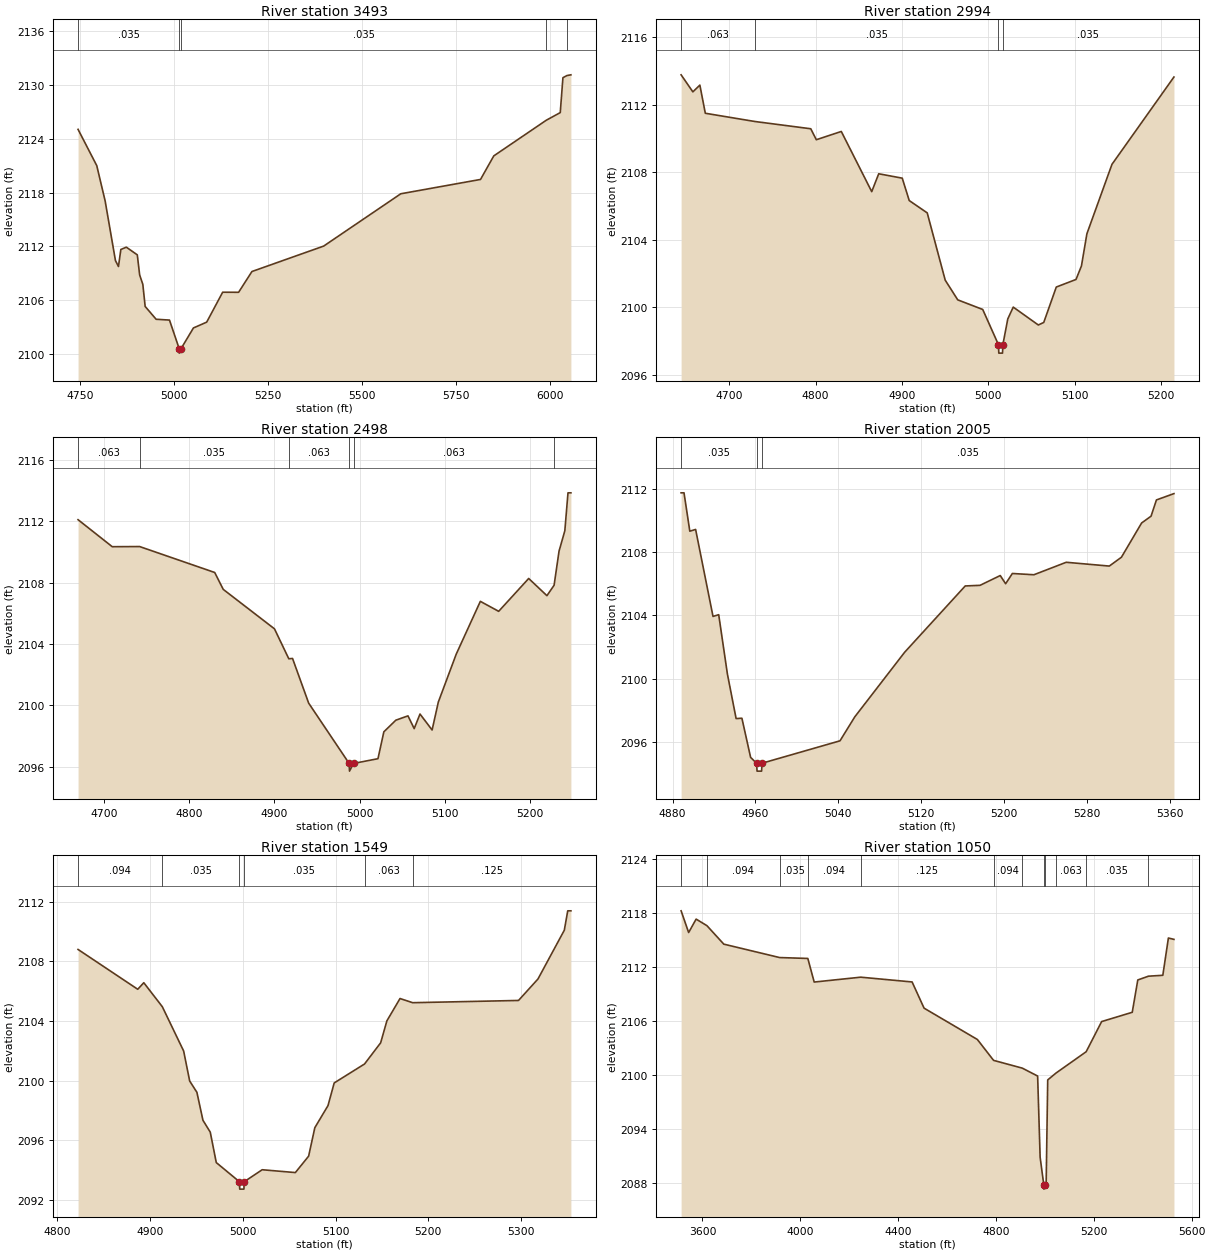
Type RM Length L Ch R = 1,3493,499,499,499
BEGIN DESCRIPTION:
Sweetwater Creek Trib 27 T8_5 6.0
END DESCRIPTION:
XS GIS Cut Line= 3
      1377754.99      6863238.01      1377960.93      6863085.76
      1378705.01      6862337.99
#Sta/Elev= 30
  4743.9 2125.06  4793.7 2121.01  4816.0 2117.06  4843.4 2110.41  4851.4 2109.75
  4857.7 2111.65  4872.3 2111.91  4901.5 2111.05  4907.8 2108.80  4916.2 2107.76
  4922.4 2105.29  4951.6 2103.86  4987.1 2103.77  5012.9 2100.58  5013.3 2100.08
  5017.9 2100.58  5050.8 2102.89  5086.1 2103.54  5128.6 2106.88  5171.0 2106.87
  5206.4 2109.19  5397.3 2112.03  5602.4 2117.87  5814.5 2119.47  5849.8 2122.10
  5989.8 2126.09  6026.6 2126.93  6033.7 2130.83  6044.5 2131.07  6054.9 2131.15
#Mann=5,-1,0
  4743.9   0.035       0  5012.9   0.035       0  5017.9   0.035       0
  5989.8   0.094       0  6044.5   0.125       0
Bank Sta=5012.9,5017.9
Exp/Cntr=0.3,0.1

Type RM Length L Ch R = 1,2994,496,496,496
BEGIN DESCRIPTION:
Sweetwater Creek Trib 27 T8_5 5.0
END DESCRIPTION:
XS GIS Cut Line= 3
      1378155.00      6863438.00      1378374.63      6863158.46
      1378505.00      6862988.00
#Sta/Elev= 30
  4644.5 2113.78  4658.1 2112.77  4666.2 2113.17  4672.5 2111.50  4730.0 2111.01
  4794.5 2110.58  4800.9 2109.93  4829.8 2110.42  4865.0 2106.85  4873.1 2107.91
  4900.3 2107.65  4908.4 2106.32  4929.2 2105.59  4950.0 2101.60  4964.5 2100.43
  4993.4 2099.86  5011.6 2097.77  5012.0 2097.27  5016.3 2097.27  5016.7 2097.77
  5022.4 2099.30  5028.7 2100.00  5057.7 2098.94  5064.0 2099.09  5078.5 2101.19
  5101.3 2101.64  5107.6 2102.44  5113.9 2104.35  5142.9 2108.47  5214.6 2113.65
#Mann=4,-1,0
  4644.5   0.063       0  4730.0   0.035       0  5011.6   0.035       0
  5016.7   0.035       0
Bank Sta=5011.6,5016.7
Exp/Cntr=0.3,0.1

Type RM Length L Ch R = 1,2498,493,493,493
BEGIN DESCRIPTION:
Sweetwater Creek Trib 27 T8_5 4.0
END DESCRIPTION:
XS GIS Cut Line= 3
      1378205.00      6863488.00      1378534.80      6863468.00
      1378704.98      6863288.02
#Sta/Elev= 30
  4669.6 2112.10  4709.7 2110.34  4741.8 2110.35  4829.9 2108.66  4839.9 2107.56
  4900.0 2104.99  4916.8 2103.04  4921.2 2103.06  4940.1 2100.15  4987.6 2096.22
  4988.0 2095.72  4992.7 2096.22  5021.4 2096.53  5028.3 2098.28  5042.4 2099.04
  5056.6 2099.32  5063.9 2098.49  5070.7 2099.44  5084.9 2098.40  5092.2 2100.22
  5113.2 2103.34  5141.5 2106.78  5163.0 2106.13  5198.2 2108.27  5219.6 2107.15
  5228.0 2107.83  5233.8 2110.05  5240.6 2111.38  5244.3 2113.85  5247.7 2113.85
#Mann=6,-1,0
  4669.6   0.063       0  4741.8   0.035       0  4916.8   0.063       0
  4987.6   0.063       0  4992.7   0.063       0  5228.0   0.035       0
Bank Sta=4987.6,4992.7
Exp/Cntr=0.3,0.1

Type RM Length L Ch R = 1,2005,456,456,456
BEGIN DESCRIPTION:
Sweetwater Creek Trib 27 T8_5 3.0
END DESCRIPTION:
XS GIS Cut Line= 3
      1378404.99      6863988.00      1378504.98      6863938.00
      1378854.98      6863838.01
#Sta/Elev= 30
  4888.2 2111.77  4891.0 2111.77  4896.6 2109.34  4902.2 2109.45  4919.0 2103.94
  4924.5 2104.05  4932.9 2100.29  4941.3 2097.47  4946.9 2097.49  4955.3 2095.01
  4961.1 2094.64  4961.5 2094.14  4965.9 2094.14  4966.3 2094.64  5041.6 2096.06
  5055.9 2097.58  5104.0 2101.67  5162.5 2105.87  5176.8 2105.91  5196.3 2106.53
  5201.5 2106.01  5208.0 2106.66  5228.8 2106.58  5260.0 2107.37  5301.6 2107.13
  5313.3 2107.69  5332.8 2109.86  5341.9 2110.29  5347.1 2111.32  5364.0 2111.72
#Mann=3,-1,0
  4888.2   0.035       0  4961.1   0.035       0  4966.3   0.035       0
Bank Sta=4961.1,4966.3
Exp/Cntr=0.3,0.1

Type RM Length L Ch R = 1,1549,499,499,499
BEGIN DESCRIPTION:
Sweetwater Creek Trib 27 T8_5 2.0
END DESCRIPTION:
XS GIS Cut Line= 3
      1378555.01      6864437.99      1378691.78      6864324.38
      1378955.02      6864087.98
#Sta/Elev= 30
  4822.2 2108.79  4886.6 2106.12  4893.1 2106.56  4913.1 2104.95  4936.1 2101.98
  4942.6 2099.97  4950.4 2099.21  4956.9 2097.34  4964.8 2096.54  4971.3 2094.50
  4996.2 2093.22  4996.6 2092.72  5001.1 2092.72  5001.5 2093.22  5020.8 2094.02
  5056.6 2093.83  5070.9 2094.93  5077.6 2096.84  5091.8 2098.32  5098.5 2099.84
  5131.2 2101.11  5148.6 2102.53  5155.3 2104.00  5169.5 2105.50  5183.1 2105.22
  5297.3 2105.37  5318.3 2106.81  5346.7 2110.08  5350.4 2111.38  5353.8 2111.38
#Mann=6,-1,0
  4822.2   0.094       0  4913.1   0.035       0  4996.2   0.035       0
  5001.5   0.035       0  5131.2   0.063       0  5183.1   0.125       0
Bank Sta=4996.2,5001.5
Exp/Cntr=0.3,0.1

Type RM Length L Ch R = 1,1050,496,496,496
BEGIN DESCRIPTION:
Sweetwater Creek Trib 27 T8_5 1.0
END DESCRIPTION:
XS GIS Cut Line= 3
      1377655.00      6864888.00      1379103.97      6864552.06
      1379355.00      6864088.00
#Sta/Elev= 30
  3512.6 2118.24  3543.4 2115.83  3574.0 2117.32  3618.2 2116.59  3687.1 2114.54
  3915.4 2113.05  4030.7 2112.95  4056.7 2110.33  4247.0 2110.87  4457.0 2110.34
  4506.0 2107.43  4723.9 2103.95  4790.2 2101.63  4907.4 2100.77  4970.3 2099.89
  4980.5 2090.87  4995.3 2087.83  4995.7 2087.33  5000.6 2087.83  5005.1 2087.83
  5011.5 2099.46  5045.3 2100.22  5168.7 2102.59  5232.0 2105.94  5357.1 2106.97
  5379.8 2110.56  5423.3 2110.98  5482.1 2111.08  5504.9 2115.22  5527.6 2115.07
#Mann=12,-1,0
  3512.6   0.035       0  3618.2   0.094       0  3915.4   0.035       0
  4030.7   0.094       0  4247.0   0.125       0  4790.2   0.094       0
  4907.4   0.035       0  4995.3   0.035       0  5000.6   0.035       0
  5045.3   0.063       0  5168.7   0.035       0  5423.3   0.125       0
Bank Sta=4995.3,5000.6
Exp/Cntr=0.3,0.1

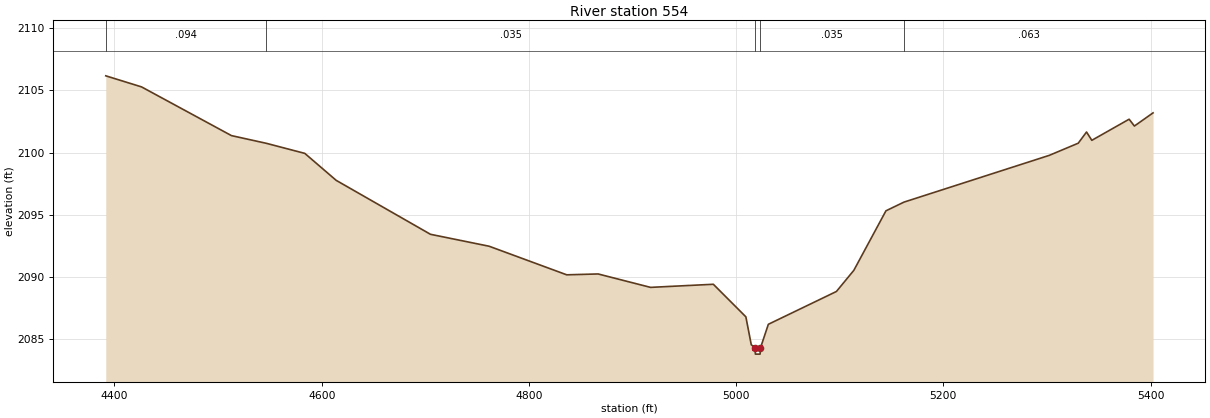
Type RM Length L Ch R = 1,554,0,0,0
BEGIN DESCRIPTION:
Sweetwater Creek Trib 27 T8_5 2713
END DESCRIPTION:
XS GIS Cut Line= 3
      1378805.03      6864838.00      1379406.71      6864928.20
      1379505.00      6864537.99
#Sta/Elev= 30
  4391.6 2106.18  4426.1 2105.29  4512.9 2101.37  4546.6 2100.75  4583.7 2099.94
  4614.0 2097.77  4705.0 2093.43  4761.6 2092.47  4836.5 2090.17  4866.8 2090.24
  4917.4 2089.16  4978.0 2089.41  5009.4 2086.79  5014.6 2084.55  5018.2 2084.29
  5018.6 2083.79  5023.1 2083.79  5023.5 2084.29  5031.1 2086.19  5096.8 2088.83
  5113.6 2090.53  5144.6 2095.32  5162.0 2096.02  5302.2 2099.78  5330.2 2100.76
  5338.2 2101.66  5343.3 2100.99  5379.3 2102.69  5384.4 2102.14  5402.4 2103.20
#Mann=5,-1,0
  4391.6   0.094       0  4546.6   0.035       0  5018.2   0.035       0
  5023.5   0.035       0  5162.0   0.063       0
Bank Sta=5018.2,5023.5
Exp/Cntr=0.3,0.1

Chan Stop Cuts=-1