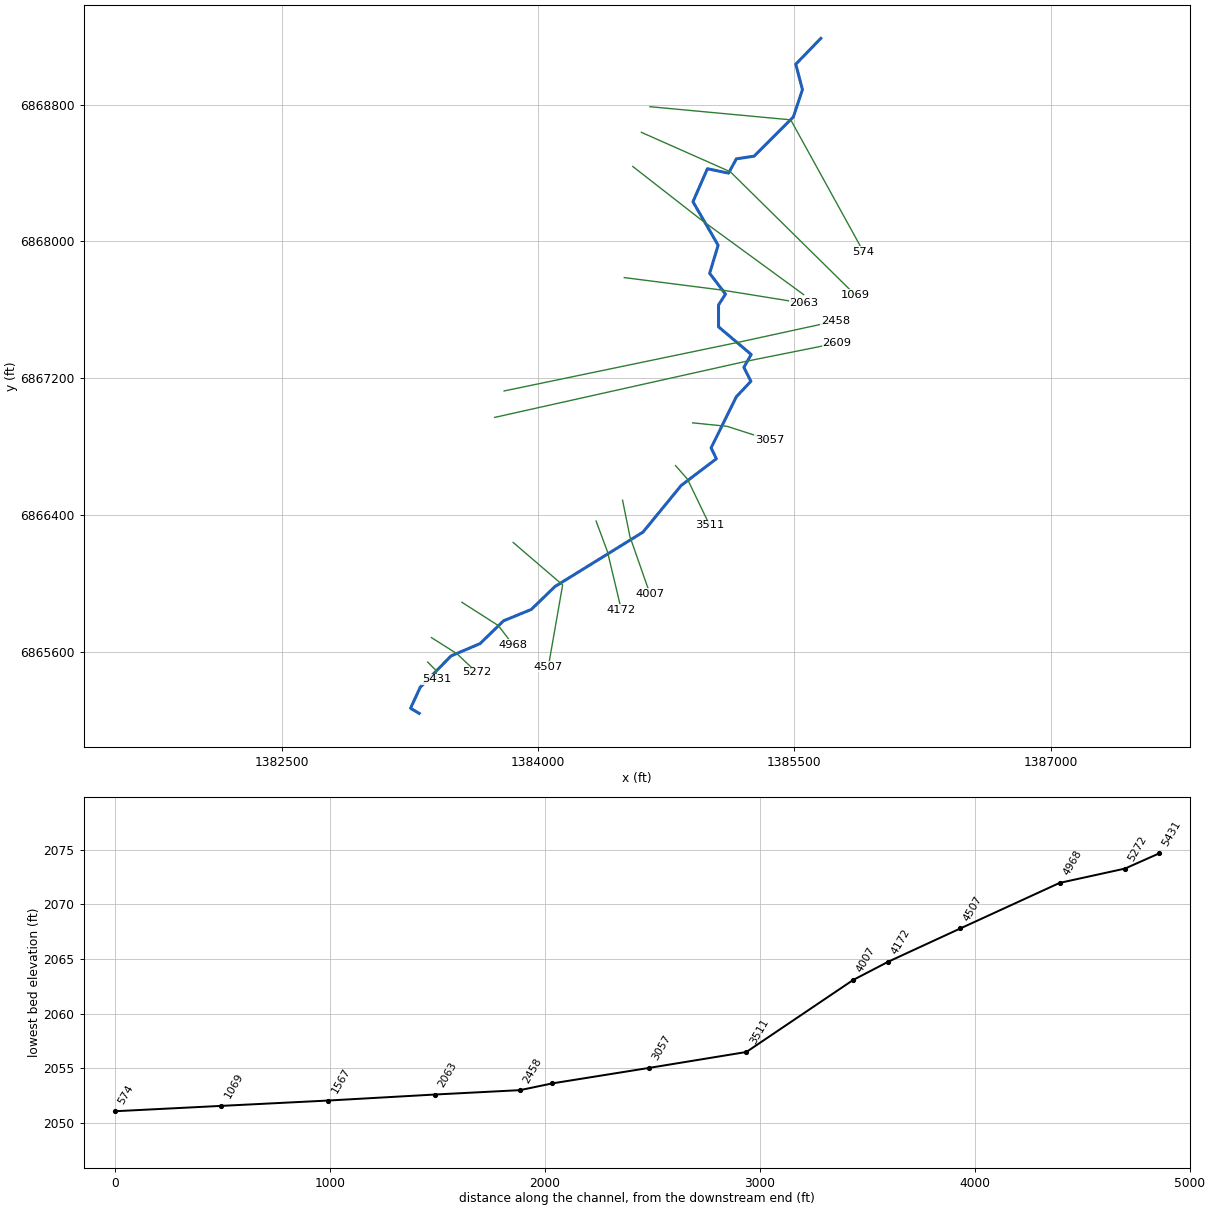
--- Sweetwater Creek Trib 27 T9.prj (project) ---

Proj Title=Sweetwater Creek Trib 27 T9 Base Level Engineering
Current Plan=p01
Default Exp/Contr=0.3,0.1
English Units
Geom File=g01
Flow File=f01
Plan File=p01
BEGIN DESCRIPTION:
Sweetwater Creek Trib 27 T9
END DESCRIPTION:

--- Sweetwater Creek Trib 27 T9.p01 (plan) ---

Plan Title=Multiple Run
Short Identifier=Multiple
Geom File=g01
Flow File=f01
Subcritical Flow
K Sum by GR= 0
Std Step Tol= 0.01
Critical Tol= 0.01
Num of Std Step Trials= 20
Max Error Tol= 0.3
Flow Tol Ratio= 0.001
Split Flow NTrial= 30
Split Flow Tol= 0.02
Split Flow Ratio= 0.02
Log Output Level= 0
Friction Slope Method= 1
Unsteady Friction Slope Method= 2
Unsteady Bridges Friction Slope Method= 1
Parabolic Critical Depth
Global Vel Dist=  1 , 1 , 1
Global Log Level= 0
CheckData=True
Encroach Param= -1, 0, 0, 0
BEGIN DESCRIPTION:
Multiple Run
END DESCRIPTION:

--- Sweetwater Creek Trib 27 T9.f01 (steady flow) ---

Flow Title=Multiple
Number of Profiles=7
Profile Names=10-year,25-year,50-year,1pct_min,100-year,1pct_plu,500-year
River Rch & RM= Sweetwater Creek,Reach-1,5431
     278     396     495     308     615    1228     963
River Rch & RM= Sweetwater Creek,Reach-1,2063
     276     392     489     303     606    1208     941
Boundary for River Rch & Prof#=Sweetwater Creek,Reach-1,1
Up Type=0
Dn Type=3
Dn Slope=0.005
Boundary for River Rch & Prof#=Sweetwater Creek,Reach-1,2
Up Type=0
Dn Type=3
Dn Slope=0.005
Boundary for River Rch & Prof#=Sweetwater Creek,Reach-1,3
Up Type=0
Dn Type=3
Dn Slope=0.005
Boundary for River Rch & Prof#=Sweetwater Creek,Reach-1,4
Up Type=0
Dn Type=3
Dn Slope=0.005
Boundary for River Rch & Prof#=Sweetwater Creek,Reach-1,5
Up Type=0
Dn Type=3
Dn Slope=0.005
Boundary for River Rch & Prof#=Sweetwater Creek,Reach-1,6
Up Type=0
Dn Type=3
Dn Slope=0.005
Boundary for River Rch & Prof#=Sweetwater Creek,Reach-1,7
Up Type=0
Dn Type=3
Dn Slope=0.005

--- Sweetwater Creek Trib 27 T9.g01 (geometry) ---

Geom Title=Existing Conditions

River Reach=Sweetwater Creek,Reach-1
Reach XY= 30
      1383305.00      6865238.00      1383254.45      6865267.72
      1383310.83      6865390.30      1383491.79      6865574.38
      1383661.06      6865646.14      1383798.94      6865779.86
      1383961.06      6865846.14      1384098.95      6865979.84
      1384614.68      6866298.78      1384837.91      6866571.56
      1385043.91      6866728.00      1385013.01      6866791.33
      1385160.55      6867090.43      1385245.83      6867181.28
      1385204.79      6867263.00      1385247.65      6867338.09
      1385056.61      6867499.83      1385056.37      6867627.55
      1385097.19      6867691.41      1385004.51      6867812.96
      1385054.06      6867977.52      1384906.82      6868231.88
      1384991.37      6868425.04      1385115.35      6868399.04
      1385160.47      6868482.68      1385264.75      6868498.53
      1385494.48      6868728.21      1385547.44      6868888.00
      1385508.46      6869036.50      1385655.00      6869188.00

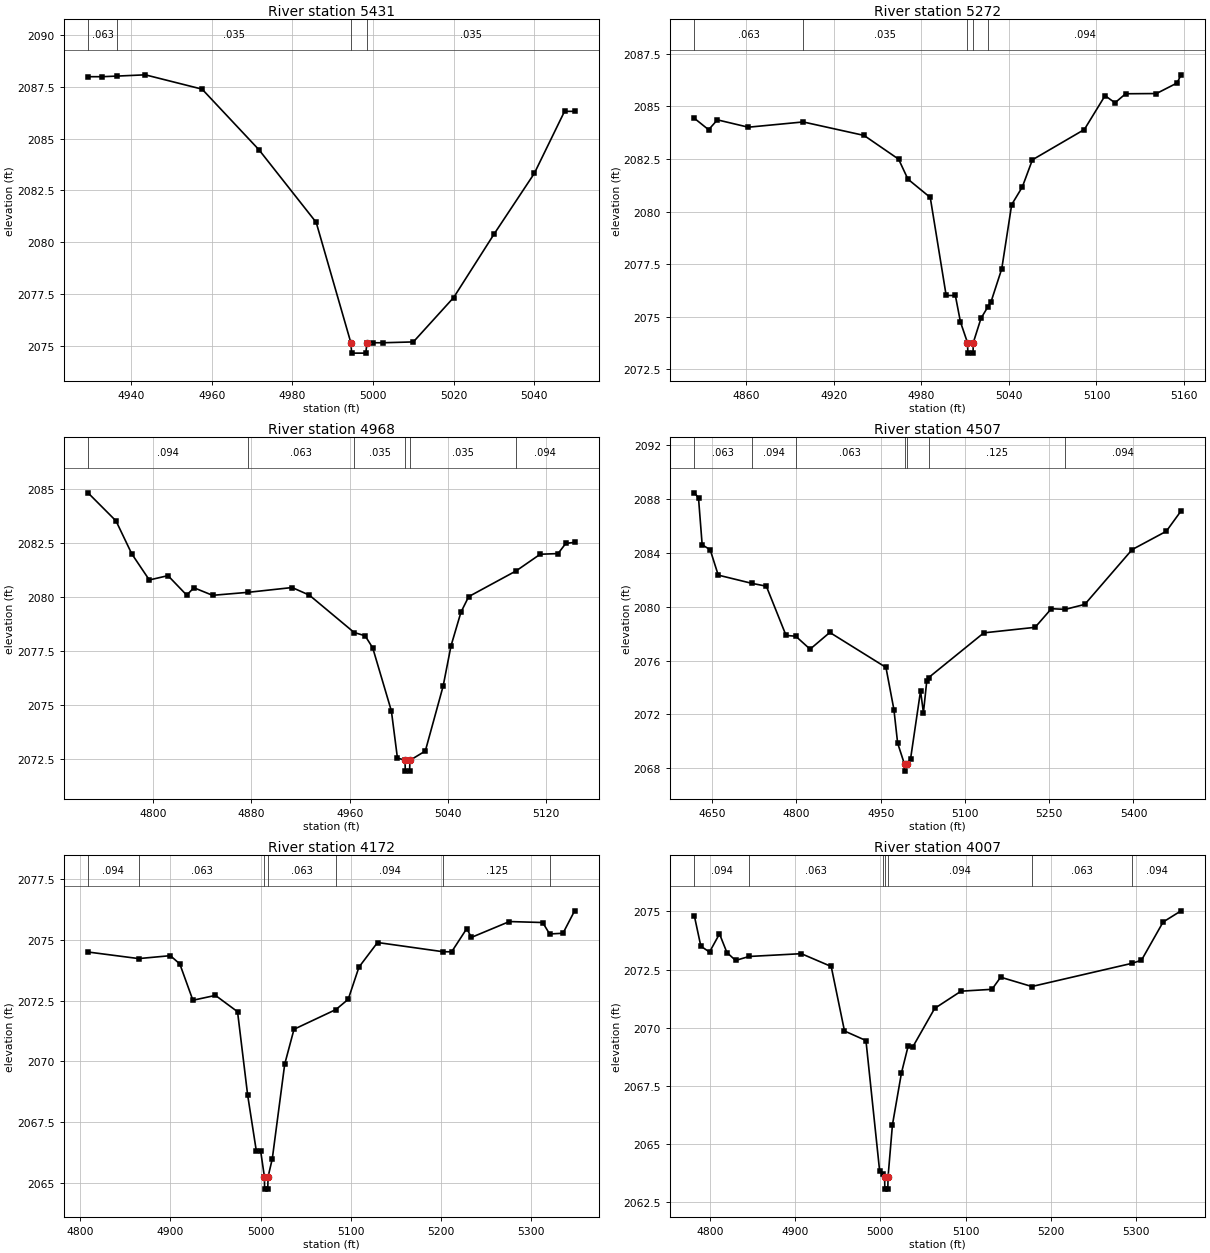
Type RM Length L Ch R = 1,5431,159,159,159
BEGIN DESCRIPTION:
Sweetwater Creek Trib 27 T9 10.0
END DESCRIPTION:
XS GIS Cut Line= 3
      1383354.99      6865538.01      1383404.98      6865488.02
      1383405.00      6865438.02
#Sta/Elev= 19
  4929.3 2087.98  4932.8 2087.98  4936.6 2088.01  4943.5 2088.07  4957.6 2087.38
  4971.7 2084.46  4985.9 2080.96  4994.5 2075.16  4994.7 2074.66  4998.2 2074.66
  4998.5 2075.16  5000.0 2075.16  5002.5 2075.16  5010.0 2075.20  5020.0 2077.34
  5030.0 2080.39  5040.0 2083.32  5047.5 2086.31  5050.0 2086.31
#Mann=4,-1,0
  4929.3   0.063       0  4936.6   0.035       0  4994.5   0.035       0
  4998.5   0.035       0
Bank Sta=4994.5,4998.5
Exp/Cntr=0.3,0.1

Type RM Length L Ch R = 1,5272,304,304,304
BEGIN DESCRIPTION:
Sweetwater Creek Trib 27 T9 3999
END DESCRIPTION:
XS GIS Cut Line= 3
      1383376.70      6865681.32      1383525.13      6865587.68
      1383640.07      6865479.26
#Sta/Elev= 30
  4824.5 2084.43  4834.2 2083.89  4840.2 2084.36  4861.4 2084.01  4899.0 2084.26
  4940.7 2083.62  4964.4 2082.49  4970.8 2081.54  4986.1 2080.67  4997.0 2076.01
  5003.3 2076.01  5006.8 2074.75  5011.6 2073.77  5011.9 2073.27  5015.4 2073.27
  5015.6 2073.77  5020.9 2074.93  5025.6 2075.47  5027.8 2075.72  5035.1 2077.28
  5041.9 2080.33  5049.2 2081.17  5056.1 2082.46  5091.7 2083.90  5105.9 2085.51
  5112.7 2085.17  5120.0 2085.60  5141.1 2085.61  5155.2 2086.11  5158.0 2086.50
#Mann=5,-1,0
  4824.5   0.063       0  4899.0   0.035       0  5011.6   0.035       0
  5015.6   0.035       0  5025.6   0.094       0
Bank Sta=5011.6,5015.6
Exp/Cntr=0.3,0.1

Type RM Length L Ch R = 1,4968,461,461,461
BEGIN DESCRIPTION:
Sweetwater Creek Trib 27 T9 9.0
END DESCRIPTION:
XS GIS Cut Line= 3
      1383555.04      6865887.98      1383768.19      6865751.68
      1383854.98      6865638.03
#Sta/Elev= 30
  4747.0 2084.83  4769.8 2083.53  4782.6 2082.01  4796.9 2080.80  4812.1 2081.00
  4827.3 2080.10  4833.2 2080.44  4848.4 2080.09  4877.5 2080.23  4913.1 2080.45
  4927.1 2080.10  4963.6 2078.37  4972.5 2078.22  4978.7 2077.66  4993.9 2074.74
  4998.8 2072.57  5005.0 2072.46  5005.2 2071.96  5008.7 2071.96  5009.0 2072.46
  5021.5 2072.89  5036.0 2075.89  5042.4 2077.75  5050.5 2079.31  5056.8 2080.03
  5095.4 2081.22  5115.0 2081.99  5129.5 2082.02  5135.8 2082.49  5143.0 2082.54
#Mann=6,-1,0
  4747.0   0.094       0  4877.5   0.063       0  4963.6   0.035       0
  5005.0   0.035       0  5009.0   0.035       0  5095.4   0.094       0
Bank Sta=5005,5009
Exp/Cntr=0.3,0.1

Type RM Length L Ch R = 1,4507,335,335,335
BEGIN DESCRIPTION:
Sweetwater Creek Trib 27 T9 8.0
END DESCRIPTION:
XS GIS Cut Line= 3
      1383854.99      6866238.01      1384144.36      6865989.56
      1384060.80      6865512.11
#Sta/Elev= 30
  4618.6 2088.43  4625.8 2088.05  4632.3 2084.58  4646.6 2084.21  4660.9 2082.33
  4720.7 2081.72  4746.5 2081.51  4781.6 2077.86  4798.9 2077.80  4824.4 2076.84
  4859.5 2078.08  4959.4 2075.49  4973.6 2072.36  4980.2 2069.88  4992.5 2068.30
  4992.7 2067.80  4996.5 2068.30  5003.3 2068.73  5021.0 2073.75  5026.1 2072.13
  5032.0 2074.46  5035.6 2074.74  5133.6 2078.05  5224.9 2078.46  5253.8 2079.84
  5278.5 2079.79  5313.3 2080.16  5397.5 2084.22  5458.4 2085.58  5484.7 2087.09
#Mann=7,-1,0
  4618.6   0.063       0  4720.7   0.094       0  4798.9   0.063       0
  4992.5   0.063       0  4996.5   0.063       0  5035.6   0.125       0
  5278.5   0.094       0
Bank Sta=4992.5,4996.5
Exp/Cntr=0.3,0.1

Type RM Length L Ch R = 1,4172,165,165,165
BEGIN DESCRIPTION:
Sweetwater Creek Trib 27 T9 4000
END DESCRIPTION:
XS GIS Cut Line= 3
      1384340.06      6866363.46      1384406.65      6866184.01
      1384487.46      6865845.42
#Sta/Elev= 30
  4808.6 2074.49  4864.8 2074.22  4899.9 2074.34  4910.4 2074.00  4924.9 2072.51
  4949.9 2072.71  4974.4 2072.04  4985.6 2068.62  4995.2 2066.33  5000.0 2066.33
  5004.2 2065.26  5004.4 2064.76  5007.9 2064.76  5008.2 2065.26  5012.9 2066.00
  5026.7 2069.89  5037.0 2071.32  5083.5 2072.13  5097.1 2072.55  5109.0 2073.87
  5129.6 2074.88  5202.6 2074.50  5211.8 2074.50  5228.5 2075.45  5233.7 2075.09
  5275.8 2075.74  5312.7 2075.70  5320.4 2075.23  5335.2 2075.26  5348.1 2076.18
#Mann=7,-1,0
  4808.6   0.094       0  4864.8   0.063       0  5004.2   0.063       0
  5008.2   0.063       0  5083.5   0.094       0  5202.6   0.125       0
  5320.4   0.094       0
Bank Sta=5004.2,5008.2
Exp/Cntr=0.3,0.1

Type RM Length L Ch R = 1,4007,496,496,496
BEGIN DESCRIPTION:
Sweetwater Creek Trib 27 T9 7.0
END DESCRIPTION:
XS GIS Cut Line= 3
      1384494.88      6866485.35      1384538.34      6866271.32
      1384654.99      6865938.04
#Sta/Elev= 30
  4781.6 2074.78  4789.1 2073.50  4799.3 2073.25  4811.0 2074.03  4819.7 2073.23
  4829.9 2072.89  4845.7 2073.06  4907.1 2073.18  4942.2 2072.63  4957.8 2069.86
  4983.0 2069.45  4999.1 2063.84  5003.4 2063.74  5004.9 2063.57  5005.2 2063.07
  5008.7 2063.07  5008.9 2063.57  5014.1 2065.83  5024.7 2068.06  5032.6 2069.22
  5037.9 2069.17  5063.7 2070.83  5094.7 2071.57  5131.0 2071.65  5141.2 2072.17
  5177.8 2071.77  5295.9 2072.77  5306.6 2072.90  5332.0 2074.54  5353.1 2075.02
#Mann=7,-1,0
  4781.6   0.094       0  4845.7   0.063       0  5003.4   0.094       0
  5004.9   0.063       0  5008.9   0.094       0  5177.8   0.063       0
  5295.9   0.094       0
Bank Sta=5004.9,5008.9
Exp/Cntr=0.3,0.1

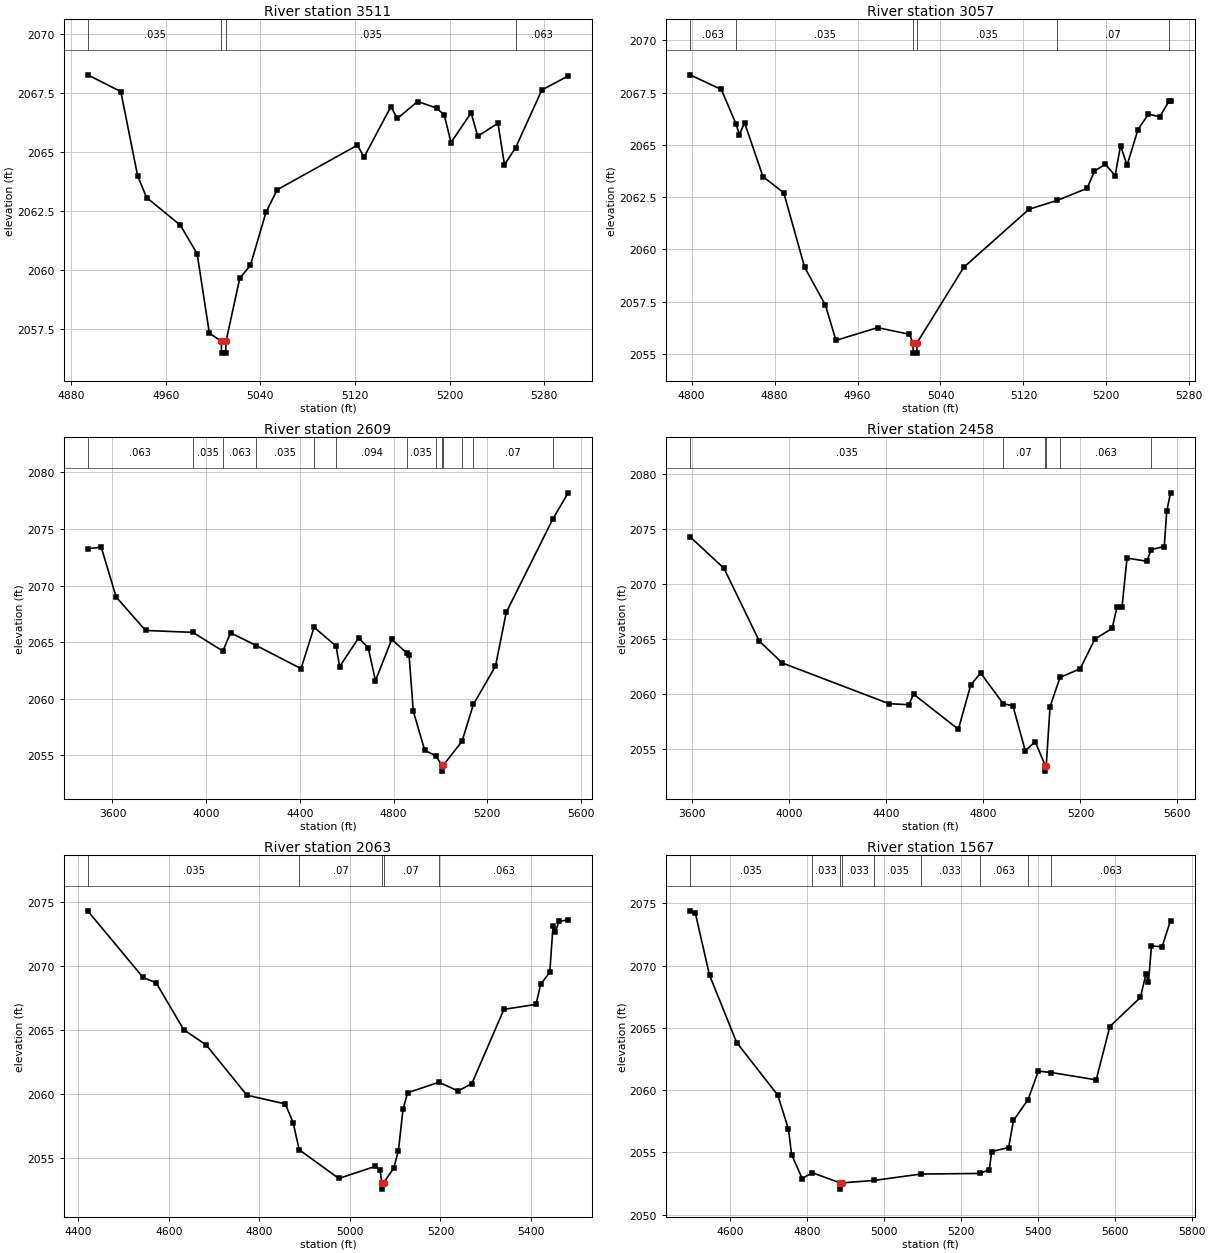
Type RM Length L Ch R = 1,3511,454,454,454
BEGIN DESCRIPTION:
Sweetwater Creek Trib 27 T9 6.0
END DESCRIPTION:
XS GIS Cut Line= 3
      1384804.99      6866688.01      1384874.78      6866608.35
      1385005.01      6866337.98
#Sta/Elev= 30
  4894.1 2068.28  4922.1 2067.57  4936.3 2064.00  4943.9 2063.08  4972.4 2061.91
  4986.6 2060.70  4996.9 2057.34  5007.0 2056.99  5007.2 2056.49  5010.7 2056.49
  5011.0 2056.99  5022.6 2059.66  5031.6 2060.21  5044.8 2062.46  5054.2 2063.41
  5122.1 2065.30  5127.6 2064.79  5150.3 2066.93  5155.8 2066.43  5172.9 2067.15
  5189.1 2066.87  5195.5 2066.57  5201.1 2065.41  5218.1 2066.67  5223.7 2065.68
  5240.8 2066.23  5246.3 2064.47  5255.7 2065.19  5277.9 2067.64  5300.1 2068.23
#Mann=4,-1,0
  4894.1   0.035       0  5007.0   0.035       0  5011.0   0.035       0
  5255.7   0.063       0
Bank Sta=5007,5011
Exp/Cntr=0.3,0.1

Type RM Length L Ch R = 1,3057,448,448,448
BEGIN DESCRIPTION:
Sweetwater Creek Trib 27 T9 5.0
END DESCRIPTION:
XS GIS Cut Line= 3
      1384905.01      6866938.00      1385105.50      6866917.79
      1385354.95      6866838.01
#Sta/Elev= 30
  4798.5 2068.35  4828.6 2067.65  4843.0 2065.98  4846.0 2065.49  4851.1 2066.05
  4868.8 2063.48  4888.9 2062.70  4909.0 2059.14  4929.1 2057.32  4939.2 2055.64
  4979.4 2056.25  5010.0 2055.93  5013.5 2055.53  5013.7 2055.03  5017.2 2055.03
  5017.5 2055.53  5062.5 2059.14  5125.5 2061.92  5152.7 2062.34  5181.5 2062.92
  5188.5 2063.74  5199.0 2064.07  5208.5 2063.53  5213.7 2064.96  5220.0 2064.02
  5230.5 2065.73  5240.6 2066.47  5251.5 2066.34  5260.7 2067.11  5261.9 2067.11
#Mann=6,-1,0
  4798.5   0.063       0  4843.0   0.035       0  5013.5   0.035       0
  5017.5   0.035       0  5152.7    0.07       0  5260.7   0.035       0
Bank Sta=5013.5,5017.5
Exp/Cntr=0.3,0.1

Type RM Length L Ch R = 1,2609,151,151,151
BEGIN DESCRIPTION:
Sweetwater Creek Trib 27 T9 4.0
END DESCRIPTION:
XS GIS Cut Line= 3
      1383746.38      6866969.85      1385215.96      6867297.68
      1385750.04      6867404.72
#Sta/Elev= 30
  3494.3 2073.25  3552.0 2073.40  3615.8 2068.99  3741.2 2066.04  3943.1 2065.87
  4071.2 2064.22  4104.2 2065.83  4214.4 2064.70  4404.8 2062.67  4460.4 2066.32
  4554.3 2064.66  4569.5 2062.85  4650.7 2065.38  4691.6 2064.50  4722.4 2061.61
  4791.9 2065.25  4856.7 2064.04  4865.8 2063.88  4883.9 2058.91  4932.5 2055.47
  4979.1 2054.97  5007.2 2054.12  5007.5 2053.62  5011.2 2054.12  5091.8 2056.25
  5140.3 2059.51  5234.7 2062.89  5280.5 2067.63  5479.5 2075.88  5544.7 2078.19
#Mann=13,-1,0
  3494.3   0.063       0  3943.1   0.035       0  4071.2   0.063       0
  4214.4   0.035       0  4460.4   0.063       0  4554.3   0.094       0
  4856.7   0.035       0  4979.1    0.07       0  5007.2    0.07       0
  5011.2    0.07       0  5091.8   0.063       0  5140.3    0.07       0
  5479.5   0.035       0
Bank Sta=5007.2,5011.2
Exp/Cntr=0.3,0.1

Type RM Length L Ch R = 1,2458,395,395,395
BEGIN DESCRIPTION:
Sweetwater Creek Trib 27 T9 3998
END DESCRIPTION:
XS GIS Cut Line= 3
      1383801.98      6867124.68      1385181.81      6867411.38
      1385740.24      6867532.94
#Sta/Elev= 30
  3590.7 2074.30  3730.8 2071.43  3876.0 2064.82  3971.1 2062.83  4410.9 2059.13
  4492.6 2059.04  4512.1 2060.00  4696.8 2056.80  4747.9 2060.84  4788.8 2061.92
  4882.0 2059.12  4921.5 2058.95  4972.6 2054.86  5013.5 2055.67  5055.1 2053.50
  5055.3 2053.00  5059.1 2053.50  5074.9 2058.87  5116.1 2061.52  5199.2 2062.31
  5259.1 2064.99  5330.8 2065.98  5351.2 2067.96  5371.7 2067.96  5392.2 2072.37
  5473.3 2072.08  5492.4 2073.14  5545.7 2073.42  5555.9 2076.62  5571.5 2078.30
#Mann=6,-1,0
  3590.7   0.035       0  4882.0    0.07       0  5055.1    0.07       0
  5059.1    0.07       0  5116.1   0.063       0  5492.4   0.094       0
Bank Sta=5055.1,5059.1
Exp/Cntr=0.3,0.1

Type RM Length L Ch R = 1,2063,496,496,496
BEGIN DESCRIPTION:
Sweetwater Creek Trib 27 T9 3.0
END DESCRIPTION:
XS GIS Cut Line= 3
      1384504.97      6867788.00      1385079.21      6867714.66
      1385554.97      6867638.00
#Sta/Elev= 30
  4421.1 2074.29  4543.3 2069.10  4572.3 2068.68  4632.8 2065.04  4683.2 2063.82
  4772.6 2059.92  4857.5 2059.24  4874.8 2057.77  4888.1 2055.67  4975.6 2053.43
  5056.5 2054.38  5066.6 2054.11  5070.5 2053.10  5070.7 2052.60  5074.6 2053.10
  5097.0 2054.25  5107.2 2055.61  5117.3 2058.81  5127.4 2060.11  5196.6 2060.93
  5238.8 2060.25  5269.2 2060.82  5340.1 2066.61  5411.0 2067.00  5421.2 2068.57
  5441.4 2069.50  5448.5 2073.11  5453.6 2072.65  5461.7 2073.46  5481.9 2073.59
#Mann=5,-1,0
  4421.1   0.035       0  4888.1    0.07       0  5070.5    0.07       0
  5074.6    0.07       0  5196.6   0.063       0
Bank Sta=5070.5,5074.6
Exp/Cntr=0.3,0.1

Type RM Length L Ch R = 1,1567,498,498,498
BEGIN DESCRIPTION:
Sweetwater Creek Trib 27 T9 2.0
END DESCRIPTION:
XS GIS Cut Line= 3
      1384555.02      6868437.99      1384953.26      6868127.30
      1385554.98      6867688.02
#Sta/Elev= 30
  4494.9 2074.41  4508.5 2074.24  4545.5 2069.24  4616.1 2063.83  4723.2 2059.60
  4750.9 2056.87  4759.0 2054.83  4786.6 2052.90  4812.9 2053.37  4885.3 2052.55
  4885.6 2052.05  4889.5 2052.55  4974.5 2052.75  5095.0 2053.26  5249.3 2053.31
  5273.5 2053.62  5279.7 2055.07  5323.7 2055.39  5336.4 2057.57  5374.5 2059.25
  5401.0 2061.53  5434.8 2061.42  5551.6 2060.83  5587.1 2065.11  5666.6 2067.45
  5681.3 2069.36  5687.5 2068.66  5695.5 2071.59  5723.0 2071.52  5745.0 2073.63
#Mann=9,-1,0
  4494.9   0.035       0  4812.9   0.033       0  4885.3   0.035       0
  4889.5   0.033       0  4974.5   0.035       0  5095.0   0.033       0
  5249.3   0.063       0  5374.5    0.07       0  5434.8   0.063       0
Bank Sta=4885.3,4889.5
Exp/Cntr=0.3,0.1

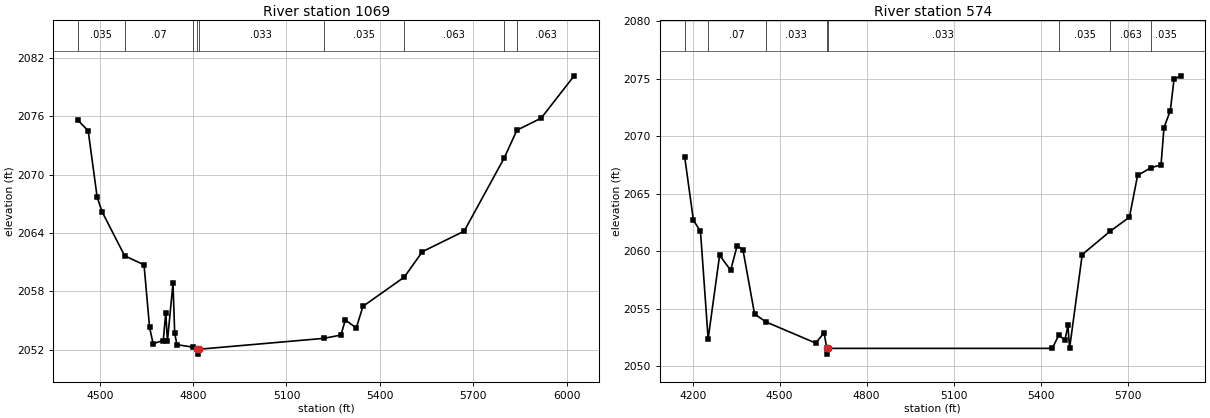
Type RM Length L Ch R = 1,1069,495,495,495
BEGIN DESCRIPTION:
Sweetwater Creek Trib 27 T9 1.0
END DESCRIPTION:
XS GIS Cut Line= 3
      1384605.04      6868637.98      1385125.37      6868407.25
      1385854.97      6867688.03
#Sta/Elev= 30
  4430.8 2075.58  4462.9 2074.51  4491.7 2067.69  4507.3 2066.21  4580.0 2061.67
  4642.3 2060.74  4660.1 2054.31  4671.4 2052.64  4704.2 2052.96  4712.1 2055.83
  4717.5 2052.88  4735.4 2058.85  4740.8 2053.74  4748.0 2052.53  4799.4 2052.28
  4814.0 2052.06  4814.3 2051.56  4818.2 2052.06  5219.7 2053.18  5275.0 2053.52
  5289.1 2055.07  5324.4 2054.25  5345.7 2056.47  5478.7 2059.48  5536.6 2062.09
  5671.0 2064.20  5799.8 2071.73  5840.5 2074.58  5918.5 2075.82  6024.5 2080.17
#Mann=9,-1,0
  4430.8   0.035       0  4580.0    0.07       0  4799.4   0.033       0
  4814.0   0.033       0  4818.2   0.033       0  5219.7   0.035       0
  5478.7   0.063       0  5799.8   0.035       0  5840.5   0.063       0
Bank Sta=4814,4818.2
Exp/Cntr=0.3,0.1

Type RM Length L Ch R = 1,574,0,0,0
BEGIN DESCRIPTION:
Sweetwater Creek Trib 27 T9 2817
END DESCRIPTION:
XS GIS Cut Line= 3
      1384655.00      6868788.00      1385478.82      6868711.13
      1385904.99      6867938.01
#Sta/Elev= 30
  4172.6 2068.23  4202.7 2062.71  4227.1 2061.75  4253.5 2052.40  4293.1 2059.67
  4331.2 2058.36  4353.4 2060.49  4373.5 2060.15  4413.6 2054.56  4452.9 2053.87
  4624.6 2052.03  4653.3 2052.94  4662.6 2051.57  4662.9 2051.07  4666.8 2051.57
  5440.3 2051.57  5462.6 2052.72  5483.9 2052.29  5494.2 2053.57  5499.9 2051.57
  5543.5 2059.73  5640.1 2061.76  5706.3 2062.98  5734.4 2066.61  5780.2 2067.28
  5815.2 2067.52  5825.5 2070.77  5847.3 2072.25  5860.0 2074.96  5882.8 2075.27
#Mann=8,-1,0
  4172.6   0.035       0  4253.5    0.07       0  4452.9   0.033       0
  4662.6   0.033       0  4666.8   0.033       0  5462.6   0.035       0
  5640.1   0.063       0  5780.2   0.035       0
Bank Sta=4662.6,4666.8
Exp/Cntr=0.3,0.1

Chan Stop Cuts=-1