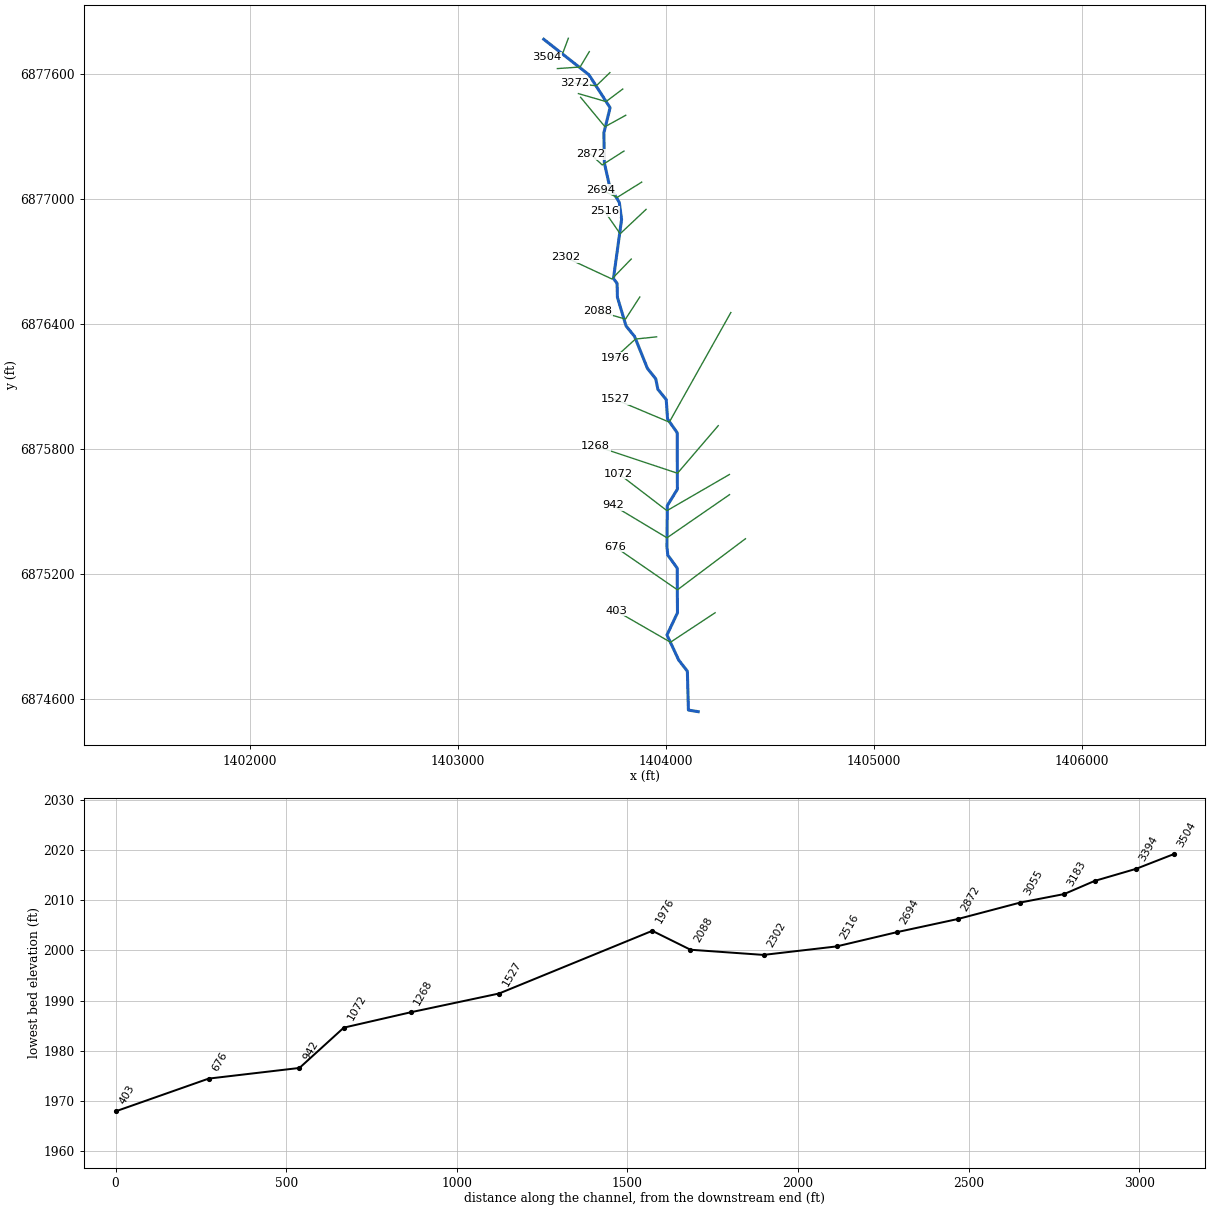
--- Sweetwater Creek Trib 28.prj (project) ---

Proj Title=Sweetwater Creek Trib 28 Base Level Engineering
Current Plan=p01
Default Exp/Contr=0.3,0.1
English Units
Geom File=g01
Flow File=f01
Plan File=p01
Y Axis Title=Elevation
X Axis Title(PF)=Main Channel Distance
X Axis Title(XS)=Station
BEGIN DESCRIPTION:
Sweetwater Creek Trib 28
END DESCRIPTION:
DSS Export Rating Curves= 0
DSS Export Rating Curve Sorted= 0
DSS Export Volume Flow Curves= 0
DXF OffsetX= 0
DXF OffsetY= 0
DXF ScaleX= 1
DXF ScaleY= 10

--- Sweetwater Creek Trib 28.p01 (plan) ---

Plan Title=Multiple Run
Short Identifier=Multiple
Geom File=g01
Flow File=f01
Subcritical Flow
K Sum by GR= 0
Std Step Tol= 0.01
Critical Tol= 0.01
Num of Std Step Trials= 20
Max Error Tol= 0.3
Flow Tol Ratio= 0.001
Split Flow NTrial= 30
Split Flow Tol= 0.02
Split Flow Ratio= 0.02
Log Output Level= 0
Friction Slope Method= 1
Unsteady Friction Slope Method= 2
Unsteady Bridges Friction Slope Method= 1
Parabolic Critical Depth
Global Vel Dist=  1 , 1 , 1
Global Log Level= 0
CheckData=True
Encroach Param= -1, 0, 0, 0
BEGIN DESCRIPTION:
Multiple Run
END DESCRIPTION:

--- Sweetwater Creek Trib 28.f01 (steady flow) ---

Flow Title=Multiple
Number of Profiles=7
Profile Names=10-year,25-year,50-year,1pct_min,100-year,1pct_plu,500-year
River Rch & RM= Sweetwater Creek,Reach-1,3504
     211     295     365     225     449     895     686
Boundary for River Rch & Prof#=Sweetwater Creek,Reach-1,1
Up Type=0
Dn Type=3
Dn Slope=0.005
Boundary for River Rch & Prof#=Sweetwater Creek,Reach-1,2
Up Type=0
Dn Type=3
Dn Slope=0.005
Boundary for River Rch & Prof#=Sweetwater Creek,Reach-1,3
Up Type=0
Dn Type=3
Dn Slope=0.005
Boundary for River Rch & Prof#=Sweetwater Creek,Reach-1,4
Up Type=0
Dn Type=3
Dn Slope=0.005
Boundary for River Rch & Prof#=Sweetwater Creek,Reach-1,5
Up Type=0
Dn Type=3
Dn Slope=0.005
Boundary for River Rch & Prof#=Sweetwater Creek,Reach-1,6
Up Type=0
Dn Type=3
Dn Slope=0.005
Boundary for River Rch & Prof#=Sweetwater Creek,Reach-1,7
Up Type=0
Dn Type=3
Dn Slope=0.005

--- Sweetwater Creek Trib 28.g01 (geometry) ---

Geom Title=Existing Conditions

River Reach=Sweetwater Creek,Reach-1
Reach XY= 30
      1403412.74      6877766.92      1403629.67      6877596.57
      1403731.40      6877438.23      1403701.54      6877317.40
      1403703.97      6877172.95      1403729.67      6877058.72
      1403775.85      6876983.37      1403786.61      6876901.60
      1403747.55      6876617.75      1403764.91      6876595.18
      1403766.65      6876527.47      1403808.16      6876390.10
      1403848.83      6876340.23      1403911.08      6876185.80
      1403950.84      6876136.28      1403961.12      6876085.82
      1404001.17      6876036.42      1404007.47      6875943.57
      1404053.78      6875877.50      1404054.79      6875606.27
      1404006.22      6875527.50      1404004.55      6875328.72
      1404008.78      6875289.57      1404053.78      6875227.50
      1404055.19      6875012.91      1404004.81      6874906.43
      1404061.11      6874785.82      1404102.65      6874732.48
      1404107.70      6874545.70      1404155.00      6874538.00

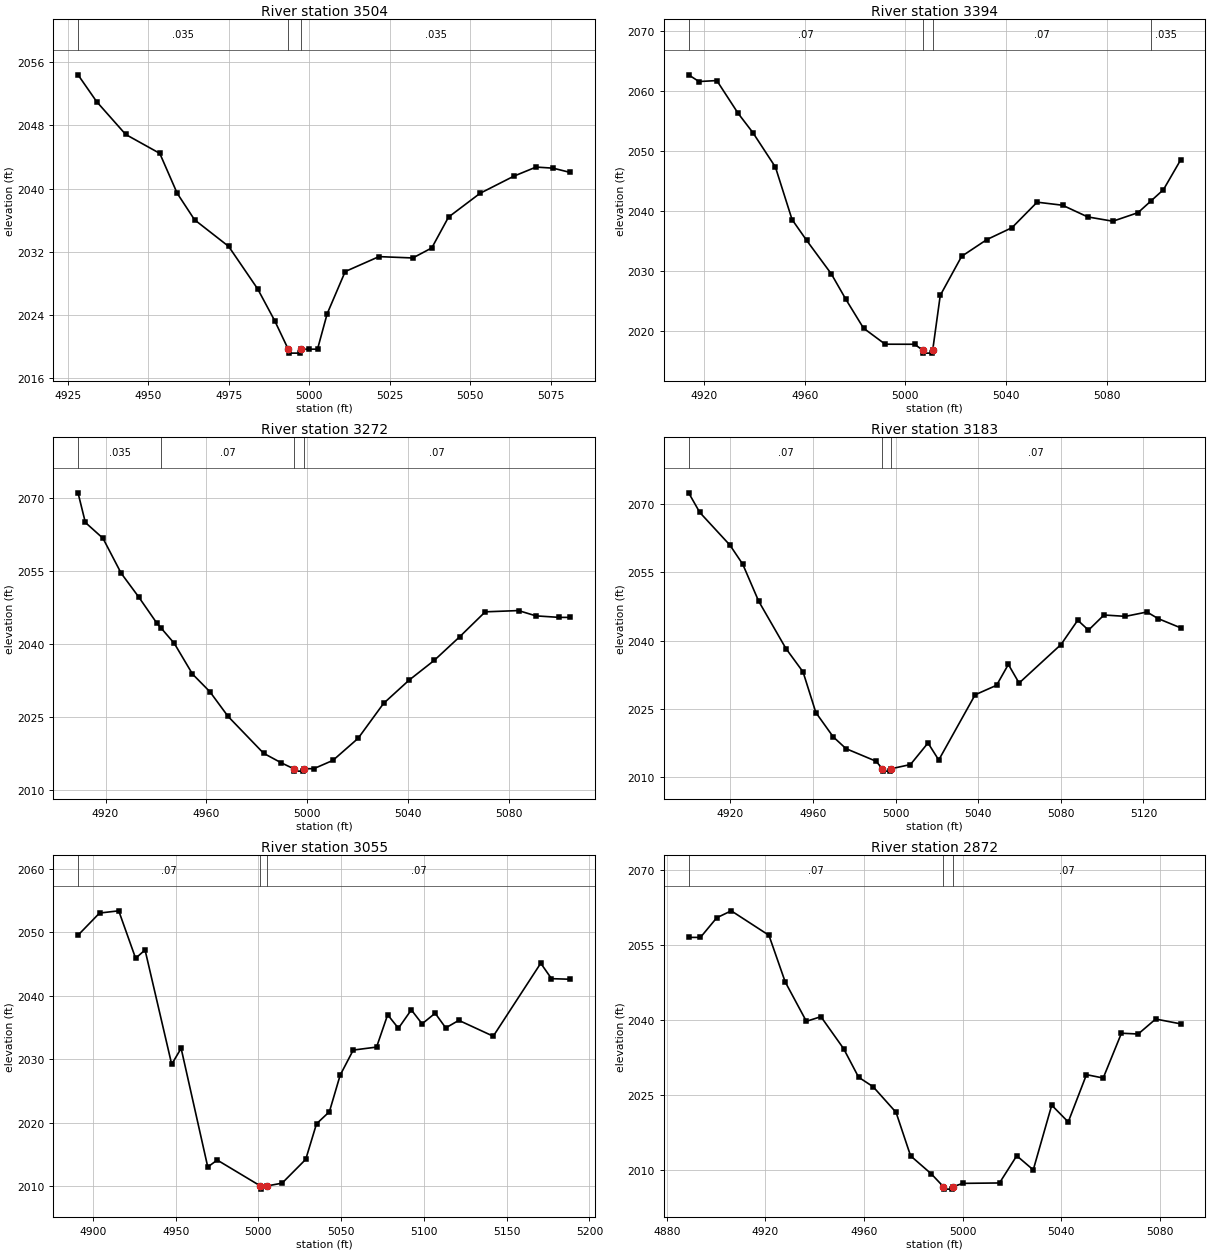
Type RM Length L Ch R = 1,3504,110,110,110
BEGIN DESCRIPTION:
Sweetwater Creek Trib 28 4260
END DESCRIPTION:
XS GIS Cut Line= 3
      1403530.78      6877771.83      1403505.71      6877704.55
      1403428.30      6877680.35
#Sta/Elev= 26
  4928.2 2054.40  4934.0 2051.00  4943.0 2046.86  4953.6 2044.46  4959.0 2039.42
  4964.4 2036.06  4975.0 2032.69  4984.0 2027.32  4989.3 2023.29  4993.5 2019.69
  4993.7 2019.19  4997.2 2019.19  4997.5 2019.69  5000.0 2019.69  5002.6 2019.69
  5005.6 2024.17  5011.2 2029.51  5021.7 2031.40  5032.2 2031.23  5038.1 2032.50
  5043.3 2036.40  5053.1 2039.41  5063.6 2041.58  5070.5 2042.73  5075.8 2042.59
  5081.1 2042.05
#Mann=3,-1,0
  4928.2   0.035       0  4993.5   0.035       0  4997.5   0.035       0
Bank Sta=4993.5,4997.5
Exp/Cntr=0.3,0.1

Type RM Length L Ch R = 1,3394,122,122,122
BEGIN DESCRIPTION:
Sweetwater Creek Trib 28 4126
END DESCRIPTION:
XS GIS Cut Line= 3
      1403631.49      6877707.63      1403587.32      6877633.72
      1403478.08      6877626.14
#Sta/Elev= 29
  4913.9 2062.73  4918.0 2061.61  4925.1 2061.77  4933.6 2056.28  4939.4 2053.10
  4948.4 2047.32  4955.0 2038.57  4960.8 2035.09  4970.6 2029.50  4976.4 2025.24
  4983.4 2020.44  4992.0 2017.76  5003.7 2017.75  5006.9 2016.77  5007.1 2016.27
  5010.6 2016.27  5010.9 2016.77  5013.9 2025.91  5022.4 2032.43  5032.4 2035.22
  5042.4 2037.21  5052.4 2041.47  5062.5 2040.96  5072.5 2039.01  5082.5 2038.29
  5092.5 2039.72  5097.5 2041.62  5102.6 2043.56  5109.5 2048.57
#Mann=4,-1,0
  4913.9    0.07       0  5006.9    0.07       0  5010.9    0.07       0
  5097.5   0.035       0
Bank Sta=5006.9,5010.9
Exp/Cntr=0.3,0.1

Type RM Length L Ch R = 1,3272,89,89,89
BEGIN DESCRIPTION:
Sweetwater Creek Trib 28 6.0
END DESCRIPTION:
XS GIS Cut Line= 3
      1403730.39      6877606.67      1403665.08      6877543.44
      1403561.50      6877555.62
#Sta/Elev= 29
  4909.1 2071.05  4912.0 2064.96  4919.0 2061.70  4926.2 2054.53  4933.1 2049.69
  4940.3 2044.31  4942.1 2043.22  4947.3 2040.09  4954.5 2033.80  4961.4 2030.17
  4968.6 2025.10  4982.7 2017.52  4989.7 2015.56  4994.6 2014.35  4994.8 2013.85
  4998.3 2013.85  4998.6 2014.35  5002.6 2014.35  5010.2 2016.06  5020.2 2020.60
  5030.3 2027.78  5040.4 2032.55  5050.4 2036.62  5060.5 2041.48  5070.6 2046.59
  5083.8 2046.85  5090.7 2045.76  5100.0 2045.45  5104.3 2045.45
#Mann=4,-1,0
  4909.1   0.035       0  4942.1    0.07       0  4994.6    0.07       0
  4998.6    0.07       0
Bank Sta=4994.6,4998.6
Exp/Cntr=0.3,0.1

Type RM Length L Ch R = 1,3183,128,128,128
BEGIN DESCRIPTION:
Sweetwater Creek Trib 28 4261
END DESCRIPTION:
XS GIS Cut Line= 3
      1403792.08      6877527.92      1403711.96      6877467.75
      1403579.26      6877506.00
#Sta/Elev= 30
  4899.8 2072.54  4905.2 2068.22  4919.8 2061.02  4926.0 2056.82  4933.7 2048.68
  4946.9 2038.25  4955.2 2033.09  4961.4 2024.14  4969.8 2018.79  4976.0 2016.19
  4990.6 2013.41  4993.6 2011.74  4993.9 2011.24  4997.4 2011.24  4997.6 2011.74
  5007.2 2012.69  5015.7 2017.44  5020.9 2013.69  5038.5 2028.05  5048.9 2030.15
  5054.6 2034.74  5059.8 2030.64  5080.1 2039.13  5088.2 2044.48  5093.4 2042.29
  5100.9 2045.63  5111.3 2045.33  5121.7 2046.29  5127.1 2044.84  5138.1 2042.79
#Mann=3,-1,0
  4899.8    0.07       0  4993.6    0.07       0  4997.6    0.07       0
Bank Sta=4993.6,4997.6
Exp/Cntr=0.3,0.1

Type RM Length L Ch R = 1,3055,183,183,183
BEGIN DESCRIPTION:
Sweetwater Creek Trib 28 5.0
END DESCRIPTION:
XS GIS Cut Line= 3
      1403806.58      6877401.96      1403706.66      6877346.91
      1403589.86      6877488.20
#Sta/Elev= 30
  4891.0 2049.53  4904.0 2053.02  4915.6 2053.37  4925.8 2045.90  4931.5 2047.21
  4947.6 2029.21  4953.3 2031.73  4969.4 2013.04  4975.1 2014.14  5001.2 2010.06
  5001.4 2009.56  5005.2 2010.06  5014.3 2010.50  5028.6 2014.25  5035.1 2019.84
  5042.9 2021.75  5049.4 2027.50  5057.3 2031.45  5071.4 2031.92  5078.1 2037.01
  5084.6 2034.88  5092.4 2037.78  5098.9 2035.58  5106.8 2037.25  5113.2 2034.94
  5121.1 2036.13  5141.9 2033.63  5170.6 2045.12  5177.1 2042.69  5188.4 2042.60
#Mann=3,-1,0
  4891.0    0.07       0  5001.2    0.07       0  5005.2    0.07       0
Bank Sta=5001.2,5005.2
Exp/Cntr=0.3,0.1

Type RM Length L Ch R = 1,2872,178,178,178
BEGIN DESCRIPTION:
Sweetwater Creek Trib 28 4.0
END DESCRIPTION:
XS GIS Cut Line= 3
      1403798.07      6877230.10      1403693.66      6877163.65
      1403637.48      6877214.91
#Sta/Elev= 30
  4888.8 2056.51  4893.6 2056.51  4900.2 2060.42  4906.1 2061.81  4921.4 2056.93
  4928.0 2047.63  4936.6 2039.76  4942.5 2040.69  4951.7 2034.32  4957.8 2028.61
  4963.7 2026.71  4973.0 2021.60  4978.9 2012.92  4987.3 2009.33  4992.2 2006.78
  4992.4 2006.28  4995.9 2006.28  4996.2 2006.78  5000.1 2007.43  5015.0 2007.51
  5022.0 2012.94  5028.7 2010.12  5036.2 2023.03  5042.9 2019.68  5050.3 2029.12
  5057.1 2028.45  5064.5 2037.39  5071.3 2037.23  5078.4 2040.22  5088.6 2039.25
#Mann=3,-1,0
  4888.8    0.07       0  4992.2    0.07       0  4996.2    0.07       0
Bank Sta=4992.2,4996.2
Exp/Cntr=0.3,0.1

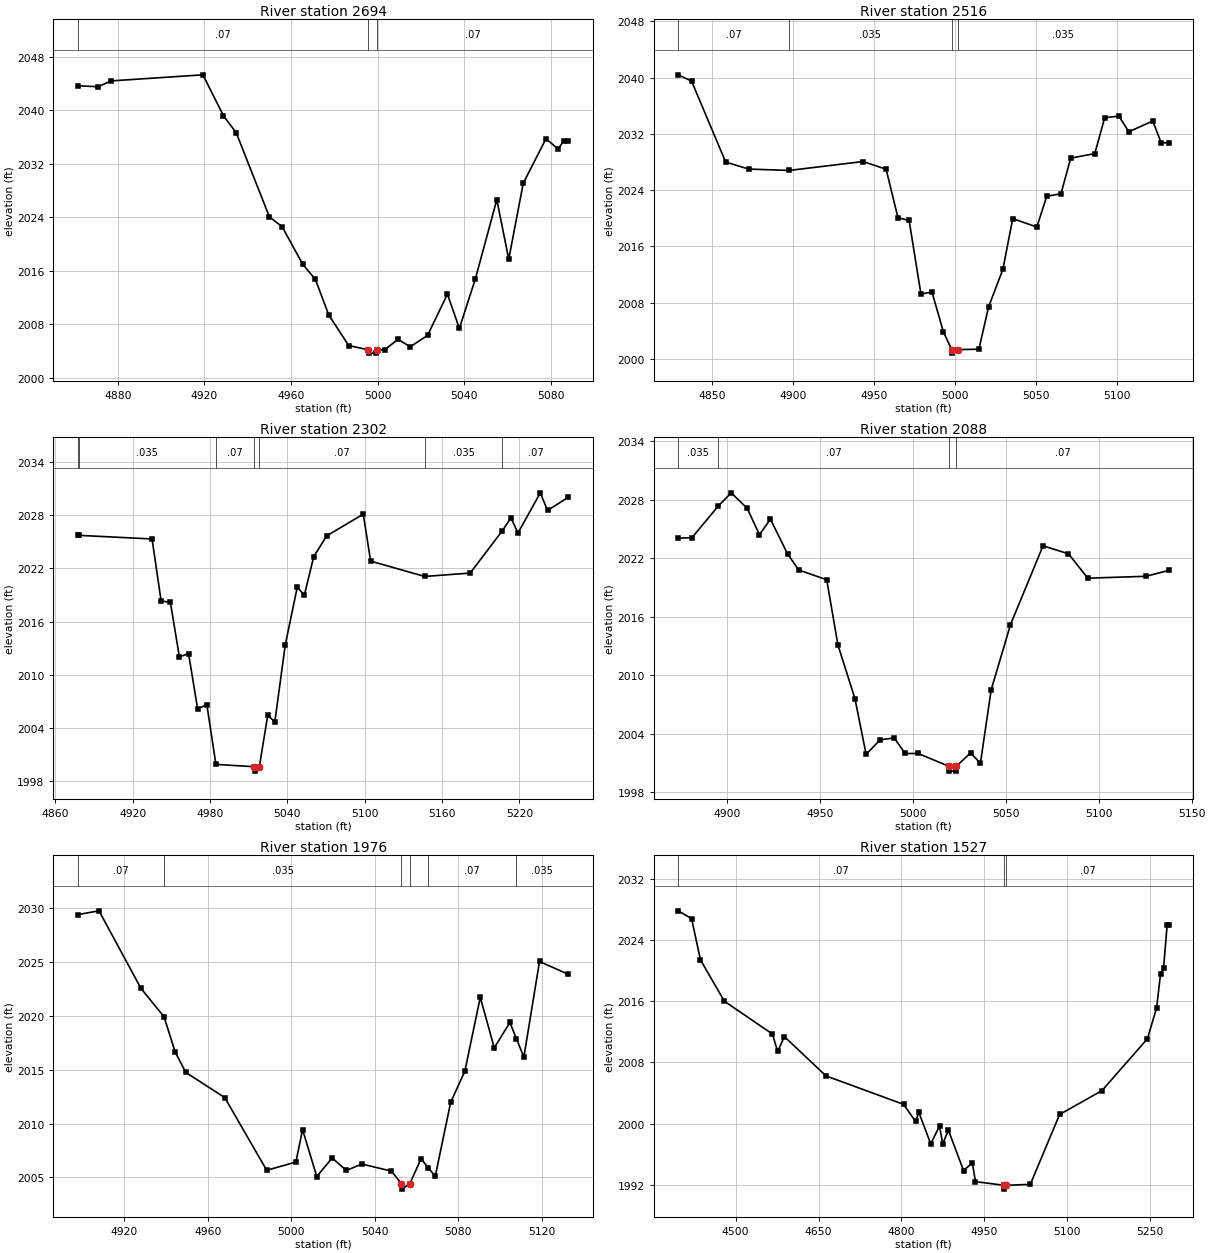
Type RM Length L Ch R = 1,2694,178,178,178
BEGIN DESCRIPTION:
Sweetwater Creek Trib 28 4262
END DESCRIPTION:
XS GIS Cut Line= 3
      1403883.23      6877080.88      1403765.78      6877007.68
      1403686.21      6877045.26
#Sta/Elev= 30
  4861.6 2043.63  4871.0 2043.49  4876.8 2044.36  4919.3 2045.27  4928.8 2039.15
  4934.7 2036.60  4950.0 2024.04  4955.9 2022.56  4965.4 2016.94  4971.2 2014.71
  4977.4 2009.38  4986.6 2004.81  4995.5 2004.17  4995.8 2003.67  4999.3 2003.67
  4999.5 2004.17  5003.2 2004.17  5009.4 2005.73  5015.0 2004.62  5023.0 2006.31
  5032.2 2012.49  5037.7 2007.37  5045.1 2014.77  5055.0 2026.61  5060.5 2017.70
  5067.2 2029.06  5077.7 2035.72  5083.3 2034.18  5085.9 2035.41  5088.0 2035.41
#Mann=3,-1,0
  4861.6    0.07       0  4995.5    0.07       0  4999.5    0.07       0
Bank Sta=4995.5,4999.5
Exp/Cntr=0.3,0.1

Type RM Length L Ch R = 1,2516,214,214,214
BEGIN DESCRIPTION:
Sweetwater Creek Trib 28 3.0
END DESCRIPTION:
XS GIS Cut Line= 3
      1403904.40      6876950.14      1403779.67      6876833.02
      1403704.76      6876941.47
#Sta/Elev= 30
  4828.9 2040.39  4837.1 2039.50  4858.2 2027.98  4872.3 2026.99  4897.3 2026.79
  4943.1 2028.06  4957.3 2026.96  4964.6 2020.07  4971.5 2019.68  4978.8 2009.22
  4985.6 2009.50  4992.7 2003.82  4997.8 2001.31  4998.0 2000.81  5001.8 2001.31
  5014.6 2001.37  5020.6 2007.40  5029.4 2012.71  5035.5 2019.94  5050.4 2018.74
  5056.5 2023.12  5065.3 2023.47  5071.3 2028.54  5086.2 2029.19  5092.3 2034.29
  5101.1 2034.52  5107.2 2032.29  5122.0 2033.82  5127.2 2030.72  5131.8 2030.72
#Mann=4,-1,0
  4828.9    0.07       0  4897.3   0.035       0  4997.8   0.035       0
  5001.8   0.035       0
Bank Sta=4997.8,5001.8
Exp/Cntr=0.3,0.1

Type RM Length L Ch R = 1,2302,214,214,214
BEGIN DESCRIPTION:
Sweetwater Creek Trib 28 2.1
END DESCRIPTION:
XS GIS Cut Line= 3
      1403832.82      6876711.46      1403740.01      6876615.88
      1403515.99      6876720.10
#Sta/Elev= 30
  4877.6 2025.74  4878.4 2025.74  4935.1 2025.33  4942.1 2018.34  4949.3 2018.17
  4956.3 2012.01  4963.4 2012.40  4970.4 2006.16  4977.6 2006.61  4984.6 1999.88
  5014.3 1999.62  5014.6 1999.12  5018.3 1999.62  5024.8 2005.42  5030.3 2004.68
  5038.4 2013.38  5047.7 2019.89  5053.2 2018.99  5060.5 2023.35  5070.6 2025.69
  5098.9 2028.13  5104.6 2022.83  5146.5 2021.10  5181.8 2021.48  5206.8 2026.27
  5213.4 2027.71  5218.9 2026.01  5236.2 2030.54  5241.8 2028.55  5257.9 2030.04
#Mann=7,-1,0
  4877.6    0.07       0  4878.4   0.035       0  4984.6    0.07       0
  5014.3    0.07       0  5018.3    0.07       0  5146.5   0.035       0
  5206.8    0.07       0
Bank Sta=5014.3,5018.3
Exp/Cntr=0.3,0.1

Type RM Length L Ch R = 1,2088,112,112,112
BEGIN DESCRIPTION:
Sweetwater Creek Trib 28 4259
END DESCRIPTION:
XS GIS Cut Line= 3
      1403874.04      6876529.16      1403805.44      6876423.11
      1403673.22      6876461.20
#Sta/Elev= 30
  4873.7 2024.06  4881.1 2024.12  4895.3 2027.38  4902.2 2028.72  4910.8 2027.13
  4917.4 2024.42  4923.3 2026.02  4932.5 2022.46  4938.5 2020.80  4953.6 2019.80
  4959.6 2013.12  4968.8 2007.58  4974.8 2001.87  4982.3 2003.36  4989.9 2003.56
  4995.8 2001.96  5002.8 2001.96  5019.3 2000.65  5019.5 2000.15  5023.0 2000.15
  5023.3 2000.65  5031.1 2002.03  5036.3 2000.94  5042.1 2008.50  5052.5 2015.19
  5070.0 2023.28  5083.7 2022.46  5094.1 2019.96  5125.3 2020.15  5137.6 2020.75
#Mann=4,-1,0
  4873.7   0.035       0  4895.3    0.07       0  5019.3    0.07       0
  5023.3    0.07       0
Bank Sta=5019.3,5023.3
Exp/Cntr=0.3,0.1

Type RM Length L Ch R = 1,1976,449,449,449
BEGIN DESCRIPTION:
Sweetwater Creek Trib 28 2.0
END DESCRIPTION:
XS GIS Cut Line= 3
      1403955.04      6876338.00      1403853.30      6876327.33
      1403755.02      6876238.02
#Sta/Elev= 30
  4897.7 2029.39  4907.8 2029.74  4927.9 2022.55  4939.0 2019.90  4944.3 2016.65
  4949.4 2014.75  4968.1 2012.41  4988.2 2005.67  5002.2 2006.43  5005.4 2009.45
  5012.2 2005.09  5019.6 2006.81  5026.4 2005.65  5033.8 2006.25  5048.0 2005.59
  5052.8 2004.42  5053.0 2003.92  5056.8 2004.42  5062.2 2006.73  5065.6 2005.92
  5069.0 2005.10  5076.4 2011.97  5083.2 2014.86  5090.6 2021.71  5097.3 2017.03
  5104.8 2019.38  5107.9 2017.89  5111.5 2016.17  5119.0 2025.04  5132.8 2023.85
#Mann=6,-1,0
  4897.7    0.07       0  4939.0   0.035       0  5052.8   0.035       0
  5056.8   0.035       0  5065.6    0.07       0  5107.9   0.035       0
Bank Sta=5052.8,5056.8
Exp/Cntr=0.3,0.1

Type RM Length L Ch R = 1,1527,259,259,259
BEGIN DESCRIPTION:
Sweetwater Creek Trib 28 0.2
END DESCRIPTION:
XS GIS Cut Line= 3
      1404311.48      6876454.64      1404015.89      6875928.37
      1403754.99      6876038.00
#Sta/Elev= 30
  4396.4 2027.78  4420.5 2026.76  4436.5 2021.38  4479.8 2015.97  4566.6 2011.69
  4576.1 2009.41  4588.2 2011.35  4663.5 2006.22  4803.8 2002.50  4825.5 2000.27
  4831.2 2001.48  4852.9 1997.35  4868.8 1999.67  4874.5 1997.34  4884.8 1999.13
  4912.2 1993.86  4928.1 1994.85  4933.8 1992.41  4985.4 1991.93  4985.7 1991.43
  4989.4 1991.93  5032.9 1992.05  5085.9 2001.18  5162.5 2004.30  5244.6 2011.06
  5261.3 2015.12  5268.4 2019.54  5273.8 2020.28  5280.3 2025.89  5283.0 2025.89
#Mann=3,-1,0
  4396.4    0.07       0  4985.4    0.07       0  4989.4    0.07       0
Bank Sta=4985.4,4989.4
Exp/Cntr=0.3,0.1

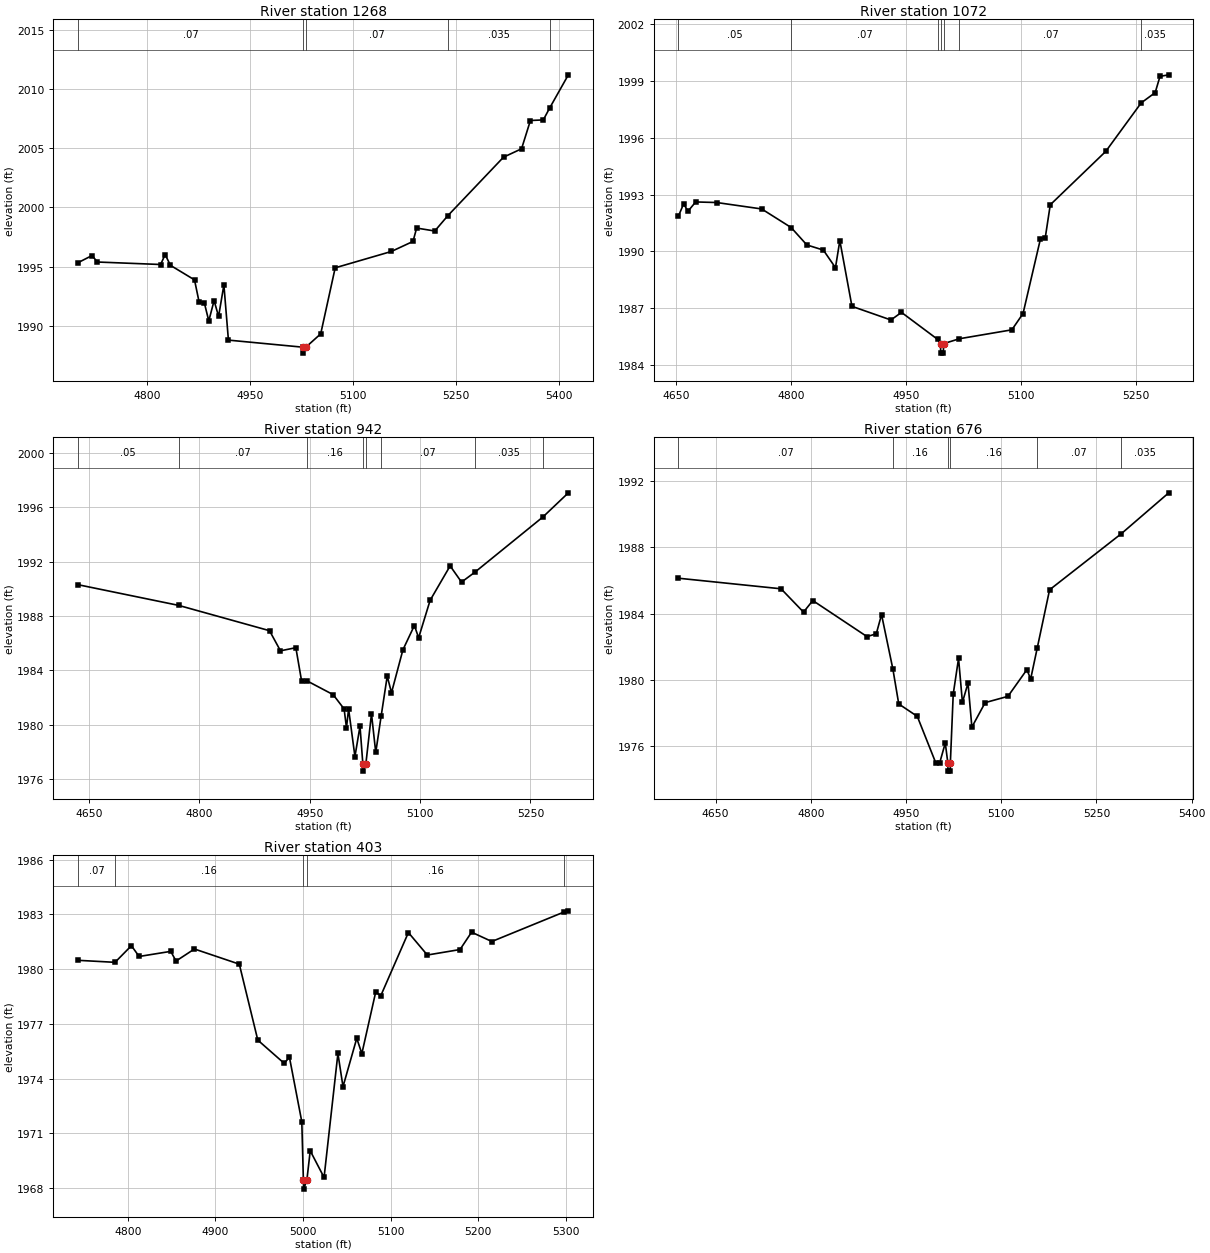
Type RM Length L Ch R = 1,1268,196,196,196
BEGIN DESCRIPTION:
Sweetwater Creek Trib 28 4263
END DESCRIPTION:
XS GIS Cut Line= 3
      1404251.05      6875911.44      1404055.09      6875682.96
      1403662.56      6875813.60
#Sta/Elev= 30
  4699.0 1995.33  4719.6 1995.94  4727.3 1995.39  4819.5 1995.18  4826.1 1996.02
  4833.8 1995.11  4868.9 1993.88  4875.5 1992.03  4883.2 1991.94  4889.7 1990.41
  4897.4 1992.13  4904.0 1990.79  4911.7 1993.46  4918.3 1988.79  5027.1 1988.19
  5027.4 1987.69  5031.1 1988.19  5052.8 1989.32  5073.9 1994.90  5155.7 1996.28
  5187.3 1997.13  5192.6 1998.26  5219.0 1998.01  5238.3 1999.32  5319.2 2004.25
  5345.5 2004.96  5358.4 2007.35  5377.2 2007.40  5386.5 2008.41  5413.7 2011.21
#Mann=5,-1,0
  4699.0    0.07       0  5027.1    0.07       0  5031.1    0.07       0
  5238.3   0.035       0  5386.5    0.07       0
Bank Sta=5027.1,5031.1
Exp/Cntr=0.3,0.1

Type RM Length L Ch R = 1,1072,130,130,130
BEGIN DESCRIPTION:
Sweetwater Creek Trib 28 4264
END DESCRIPTION:
XS GIS Cut Line= 3
      1404304.86      6875677.05      1404004.57      6875503.18
      1403772.30      6875680.96
#Sta/Elev= 30
  4653.0 1991.85  4659.9 1992.51  4665.6 1992.12  4675.6 1992.61  4702.9 1992.58
  4761.7 1992.24  4800.1 1991.26  4820.6 1990.34  4842.1 1990.07  4857.9 1989.14
  4863.6 1990.57  4879.4 1987.10  4930.2 1986.38  4944.0 1986.78  4991.0 1985.36
  4994.9 1985.13  4995.1 1984.63  4998.6 1984.63  4998.9 1985.13  5019.6 1985.39
  5087.9 1985.86  5102.5 1986.72  5125.2 1990.66  5131.5 1990.73  5138.0 1992.46
  5210.4 1995.28  5256.6 1997.84  5274.8 1998.38  5281.1 1999.24  5292.5 1999.32
#Mann=7,-1,0
  4653.0    0.05       0  4800.1    0.07       0  4991.0    0.16       0
  4994.9    0.07       0  4998.9    0.16       0  5019.6    0.07       0
  5256.6   0.035       0
Bank Sta=4994.9,4998.9
Exp/Cntr=0.3,0.1

Type RM Length L Ch R = 1,942,266,266,266
BEGIN DESCRIPTION:
Sweetwater Creek Trib 28 0.1
END DESCRIPTION:
XS GIS Cut Line= 3
      1404305.31      6875580.19      1404004.86      6875372.94
      1403746.23      6875528.11
#Sta/Elev= 30
  4635.0 1990.30  4771.8 1988.78  4895.4 1986.92  4910.3 1985.44  4931.2 1985.67
  4939.1 1983.19  4946.8 1983.22  4981.9 1982.22  4996.8 1981.17  5000.0 1979.79
  5002.9 1981.17  5011.5 1977.67  5018.4 1979.90  5022.3 1977.10  5022.5 1976.60
  5026.3 1977.10  5034.0 1980.81  5039.8 1977.97  5047.1 1980.63  5055.4 1983.58
  5061.2 1982.36  5076.7 1985.51  5092.3 1987.30  5098.1 1986.40  5113.7 1989.15
  5140.9 1991.68  5156.4 1990.49  5174.6 1991.22  5266.9 1995.27  5301.6 1997.05
#Mann=8,-1,0
  4635.0    0.05       0  4771.8    0.07       0  4946.8    0.16       0
  5022.3    0.07       0  5026.3    0.16       0  5047.1    0.07       0
  5174.6   0.035       0  5266.9    0.07       0
Bank Sta=5022.3,5026.3
Exp/Cntr=0.3,0.1

Type RM Length L Ch R = 1,676,273,273,273
BEGIN DESCRIPTION:
Sweetwater Creek Trib 28 4265
END DESCRIPTION:
XS GIS Cut Line= 3
      1404381.71      6875368.48      1404055.06      6875123.01
      1403755.35      6875329.41
#Sta/Elev= 30
  4591.4 1986.14  4753.2 1985.50  4788.6 1984.09  4803.2 1984.79  4888.6 1982.61
  4903.2 1982.78  4911.5 1983.94  4929.4 1980.64  4938.6 1978.54  4967.8 1977.79
  4996.9 1974.98  5003.1 1974.98  5011.9 1976.18  5015.9 1974.98  5016.2 1974.48
  5019.7 1974.48  5019.9 1974.98  5024.4 1979.13  5032.8 1981.29  5038.9 1978.64
  5047.7 1979.80  5053.8 1977.14  5074.7 1978.62  5110.6 1979.00  5140.4 1980.61
  5146.4 1980.05  5156.8 1981.93  5176.2 1985.44  5289.2 1988.83  5363.9 1991.30
#Mann=6,-1,0
  4591.4    0.07       0  4929.4    0.16       0  5015.9    0.07       0
  5019.9    0.16       0  5156.8    0.07       0  5289.2   0.035       0
Bank Sta=5015.9,5019.9
Exp/Cntr=0.3,0.1

Type RM Length L Ch R = 1,403,0,0,0
BEGIN DESCRIPTION:
Sweetwater Creek Trib 28 4266
END DESCRIPTION:
XS GIS Cut Line= 3
      1404235.88      6875013.01      1404021.60      6874871.48
      1403759.33      6875022.62
#Sta/Elev= 30
  4743.2 1980.48  4785.5 1980.37  4804.2 1981.28  4813.0 1980.69  4849.1 1980.97
  4855.1 1980.44  4876.1 1981.10  4927.3 1980.27  4948.4 1976.11  4978.5 1974.84
  4984.5 1975.17  4998.6 1971.64  5000.4 1968.45  5000.7 1967.95  5004.4 1968.45
  5008.2 1970.05  5024.0 1968.59  5039.8 1975.38  5045.6 1973.56  5061.3 1976.21
  5067.1 1975.37  5082.9 1978.74  5088.7 1978.54  5120.2 1982.00  5141.8 1980.77
  5179.1 1981.07  5192.3 1982.02  5215.4 1981.51  5298.0 1983.13  5302.7 1983.19
#Mann=5,-1,0
  4743.2    0.07       0  4785.5    0.16       0  5000.4    0.07       0
  5004.4    0.16       0  5298.0    0.07       0
Bank Sta=5000.4,5004.4
Exp/Cntr=0.3,0.1

Chan Stop Cuts=-1