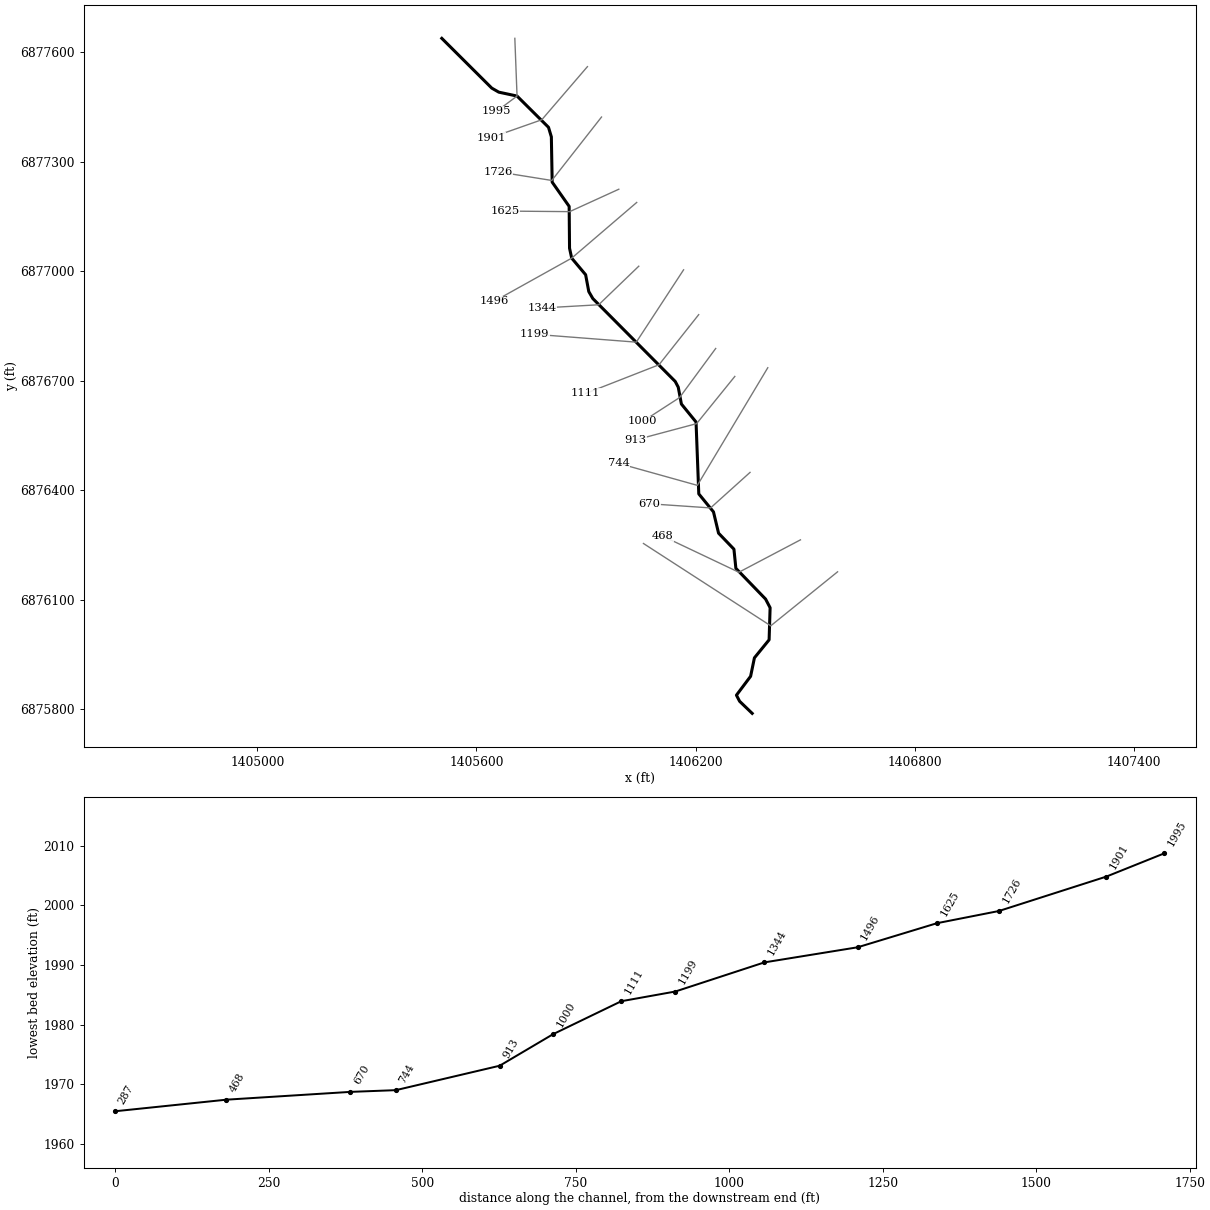
--- Sweetwater Creek Trib 29.prj (project) ---

Proj Title=Sweetwater Creek Trib 29 Base Level Engineering
Current Plan=p01
Default Exp/Contr=0.3,0.1
English Units
Geom File=g01
Flow File=f01
Plan File=p01
Y Axis Title=Elevation
X Axis Title(PF)=Main Channel Distance
X Axis Title(XS)=Station
BEGIN DESCRIPTION:
Sweetwater Creek Trib 29
END DESCRIPTION:
DSS Export Rating Curves= 0
DSS Export Rating Curve Sorted= 0
DSS Export Volume Flow Curves= 0
DXF OffsetX= 0
DXF OffsetY= 0
DXF ScaleX= 1
DXF ScaleY= 10

--- Sweetwater Creek Trib 29.p01 (plan) ---

Plan Title=Multiple Run
Short Identifier=Multiple
Geom File=g01
Flow File=f01
Subcritical Flow
K Sum by GR= 0
Std Step Tol= 0.01
Critical Tol= 0.01
Num of Std Step Trials= 20
Max Error Tol= 0.3
Flow Tol Ratio= 0.001
Split Flow NTrial= 30
Split Flow Tol= 0.02
Split Flow Ratio= 0.02
Log Output Level= 0
Friction Slope Method= 1
Unsteady Friction Slope Method= 2
Unsteady Bridges Friction Slope Method= 1
Parabolic Critical Depth
Global Vel Dist=  1 , 1 , 1
Global Log Level= 0
CheckData=True
Encroach Param= -1, 0, 0, 0
BEGIN DESCRIPTION:
Multiple Run
END DESCRIPTION:

--- Sweetwater Creek Trib 29.f01 (steady flow) ---

Flow Title=Multiple
Number of Profiles=7
Profile Names=10-year,25-year,50-year,1pct_min,100-year,1pct_plu,500-year
River Rch & RM= Sweetwater Creek,Reach-1,1995
      60      77      90      53     105     209     144
River Rch & RM= Sweetwater Creek,Reach-1,468
      76      99     116      69     137     274     193
Boundary for River Rch & Prof#=Sweetwater Creek,Reach-1,1
Up Type=0
Dn Type=3
Dn Slope=0.005
Boundary for River Rch & Prof#=Sweetwater Creek,Reach-1,2
Up Type=0
Dn Type=3
Dn Slope=0.005
Boundary for River Rch & Prof#=Sweetwater Creek,Reach-1,3
Up Type=0
Dn Type=3
Dn Slope=0.005
Boundary for River Rch & Prof#=Sweetwater Creek,Reach-1,4
Up Type=0
Dn Type=3
Dn Slope=0.005
Boundary for River Rch & Prof#=Sweetwater Creek,Reach-1,5
Up Type=0
Dn Type=3
Dn Slope=0.005
Boundary for River Rch & Prof#=Sweetwater Creek,Reach-1,6
Up Type=0
Dn Type=3
Dn Slope=0.005
Boundary for River Rch & Prof#=Sweetwater Creek,Reach-1,7
Up Type=0
Dn Type=3
Dn Slope=0.005

--- Sweetwater Creek Trib 29.g01 (geometry) ---

Geom Title=Existing Conditions

River Reach=Sweetwater Creek,Reach-1
Reach XY= 30
      1405505.00      6877638.00      1405641.79      6877501.63
      1405661.05      6877490.53      1405711.07      6877479.85
      1405797.19      6877394.21      1405805.02      6877368.01
      1405807.27      6877243.94      1405853.77      6877177.49
      1405854.81      6877062.92      1405860.71      6877035.65
      1405898.86      6876990.17      1405907.50      6876944.03
      1405918.62      6876924.78      1406144.24      6876697.68
      1406152.50      6876681.97      1406161.14      6876635.83
      1406201.25      6876586.45      1406208.74      6876389.55
      1406248.97      6876340.22      1406262.91      6876281.85
      1406305.00      6876238.00      1406310.33      6876185.49
      1406391.66      6876101.30      1406404.07      6876077.52
      1406401.33      6875989.59      1406361.09      6875940.17
      1406350.67      6875889.62      1406311.87      6875837.88
      1406320.53      6875821.17      1406355.00      6875788.00

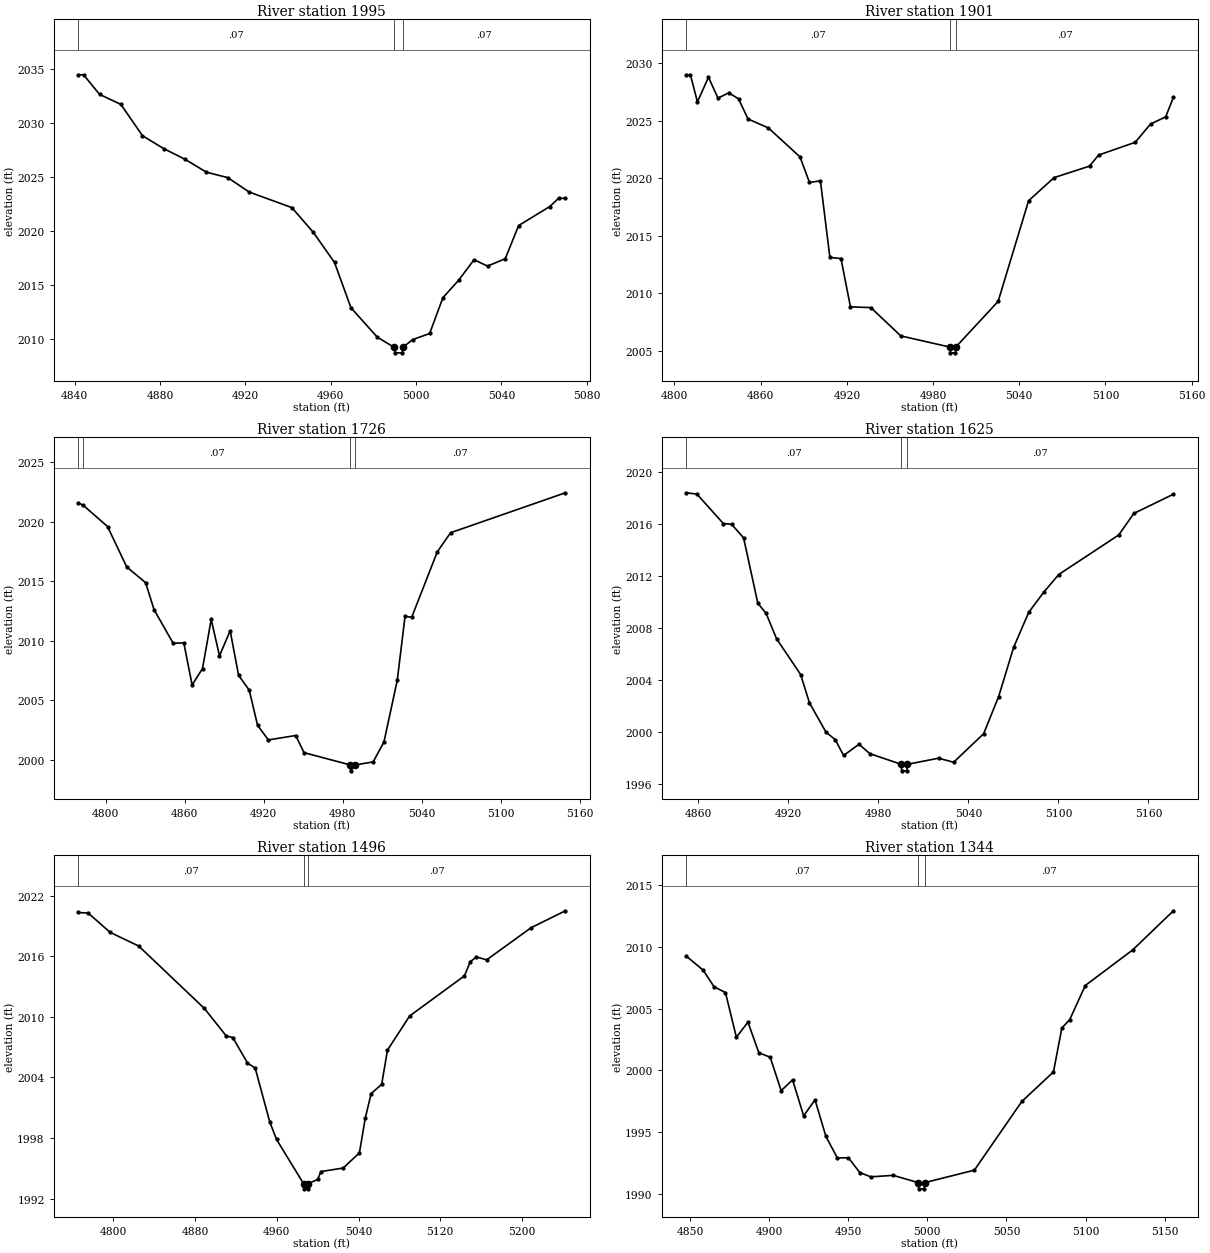
Type RM Length L Ch R = 1,1995,94,94,94
BEGIN DESCRIPTION:
Sweetwater Creek Trib 29 2.0
END DESCRIPTION:
XS GIS Cut Line= 3
      1405705.00      6877638.03      1405711.07      6877479.85
      1405654.97      6877437.98
#Sta/Elev= 30
  4841.7 2034.44  4844.2 2034.44  4851.7 2032.63  4861.7 2031.70  4871.8 2028.81
  4881.8 2027.61  4891.8 2026.62  4901.8 2025.43  4911.8 2024.93  4921.8 2023.60
  4941.8 2022.16  4951.8 2019.89  4961.8 2017.09  4969.5 2012.90  4981.8 2010.19
  4989.8 2009.23  4990.1 2008.73  4993.6 2008.73  4993.8 2009.23  4998.4 2009.95
  5006.4 2010.52  5012.6 2013.83  5020.0 2015.45  5027.2 2017.34  5033.5 2016.75
  5041.8 2017.43  5048.1 2020.50  5062.7 2022.26  5066.8 2023.02  5070.0 2023.02
#Mann=3,-1,0
  4841.7    0.07       0  4989.8    0.07       0  4993.8    0.07       0
Bank Sta=4989.8,4993.8
Exp/Cntr=0.3,0.1

Type RM Length L Ch R = 1,1901,175,175,175
BEGIN DESCRIPTION:
Sweetwater Creek Trib 29 4186
END DESCRIPTION:
XS GIS Cut Line= 3
      1405903.81      6877560.45      1405778.86      6877414.93
      1405639.93      6877365.99
#Sta/Elev= 30
  4808.2 2029.01  4811.1 2029.01  4816.0 2026.65  4823.7 2028.80  4830.3 2026.98
  4837.8 2027.44  4844.6 2026.92  4851.2 2025.17  4865.4 2024.39  4887.4 2021.87
  4894.0 2019.65  4901.6 2019.79  4908.2 2013.13  4915.9 2013.04  4922.5 2008.84
  4936.7 2008.77  4957.6 2006.31  4991.8 2005.34  4992.1 2004.84  4995.6 2004.84
  4995.8 2005.34  5025.3 2009.31  5046.5 2018.06  5064.2 2020.07  5088.9 2021.07
  5095.2 2022.03  5120.7 2023.14  5131.4 2024.73  5141.9 2025.35  5147.3 2027.05
#Mann=3,-1,0
  4808.2    0.07       0  4991.8    0.07       0  4995.8    0.07       0
Bank Sta=4991.8,4995.8
Exp/Cntr=0.3,0.1

Type RM Length L Ch R = 1,1726,101,101,101
BEGIN DESCRIPTION:
Sweetwater Creek Trib 29 3985
END DESCRIPTION:
XS GIS Cut Line= 3
      1405942.38      6877422.34      1405806.23      6877248.51
      1405658.92      6877272.18
#Sta/Elev= 30
  4779.2 2021.60  4783.1 2021.38  4801.5 2019.60  4816.0 2016.21  4830.4 2014.88
  4836.8 2012.61  4851.3 2009.79  4859.4 2009.82  4865.7 2006.28  4873.6 2007.66
  4880.2 2011.79  4886.5 2008.73  4894.6 2010.84  4901.0 2007.09  4909.1 2005.84
  4915.4 2002.89  4923.6 2001.66  4944.4 2002.03  4950.7 2000.59  4985.7 1999.56
  4986.0 1999.06  4989.7 1999.56  5003.2 1999.81  5011.4 2001.49  5021.5 2006.67
  5027.4 2012.04  5032.5 2011.98  5051.9 2017.47  5062.0 2019.08  5149.2 2022.44
#Mann=4,-1,0
  4779.2   0.035       0  4783.1    0.07       0  4985.7    0.07       0
  4989.7    0.07       0
Bank Sta=4985.7,4989.7
Exp/Cntr=0.3,0.1

Type RM Length L Ch R = 1,1625,129,129,129
BEGIN DESCRIPTION:
Sweetwater Creek Trib 29 4185
END DESCRIPTION:
XS GIS Cut Line= 3
      1405989.72      6877224.49      1405855.18      6877163.07
      1405678.58      6877164.59
#Sta/Elev= 30
  4852.1 2018.37  4859.2 2018.27  4876.8 2016.01  4882.3 2015.95  4890.3 2014.91
  4899.8 2009.88  4905.3 2009.11  4912.3 2007.15  4928.3 2004.41  4934.2 2002.23
  4945.2 1999.98  4951.4 1999.40  4956.9 1998.19  4967.2 1999.05  4974.4 1998.33
  4995.3 1997.51  4995.6 1997.01  4999.1 1997.01  4999.3 1997.51  5020.2 1997.98
  5030.2 1997.67  5050.2 1999.86  5060.2 2002.72  5070.2 2006.50  5080.2 2009.18
  5090.2 2010.73  5100.2 2012.09  5140.2 2015.13  5150.2 2016.78  5176.6 2018.26
#Mann=3,-1,0
  4852.1    0.07       0  4995.3    0.07       0  4999.3    0.07       0
Bank Sta=4995.3,4999.3
Exp/Cntr=0.3,0.1

Type RM Length L Ch R = 1,1496,152,152,152
BEGIN DESCRIPTION:
Sweetwater Creek Trib 29 1.0
END DESCRIPTION:
XS GIS Cut Line= 3
      1406038.76      6877188.27      1405860.71      6877035.65
      1405648.90      6876917.59
#Sta/Elev= 30
  4765.5 2020.34  4775.3 2020.28  4796.8 2018.37  4824.7 2017.02  4889.0 2010.84
  4910.3 2008.13  4916.9 2007.95  4931.2 2005.44  4938.8 2004.92  4953.1 1999.58
  4959.7 1997.86  4986.2 1993.47  4986.5 1992.97  4990.0 1992.97  4990.2 1993.47
  5000.0 1993.90  5003.1 1994.68  5024.9 1995.03  5040.8 1996.53  5046.6 1999.99
  5052.3 2002.41  5062.6 2003.31  5068.3 2006.71  5090.0 2010.09  5143.7 2014.07
  5149.4 2015.47  5155.4 2015.94  5165.4 2015.65  5208.9 2018.83  5242.5 2020.51
#Mann=3,-1,0
  4765.5    0.07       0  4986.2    0.07       0  4990.2    0.07       0
Bank Sta=4986.2,4990.2
Exp/Cntr=0.3,0.1

Type RM Length L Ch R = 1,1344,145,145,145
BEGIN DESCRIPTION:
Sweetwater Creek Trib 29 4184
END DESCRIPTION:
XS GIS Cut Line= 3
      1406044.40      6877013.54      1405934.61      6876907.84
      1405779.36      6876899.01
#Sta/Elev= 30
  4847.6 2009.24  4858.3 2008.10  4865.2 2006.76  4872.4 2006.29  4879.3 2002.68
  4886.6 2003.90  4893.5 2001.43  4900.7 2001.06  4907.6 1998.36  4914.8 1999.24
  4921.8 1996.33  4929.0 1997.62  4935.9 1994.66  4943.1 1992.93  4950.1 1992.94
  4957.3 1991.75  4964.2 1991.40  4978.4 1991.52  4994.3 1990.93  4994.5 1990.43
  4998.0 1990.43  4998.3 1990.93  5029.7 1991.94  5059.7 1997.49  5079.7 1999.88
  5085.0 2003.43  5090.0 2004.11  5099.8 2006.86  5129.8 2009.74  5155.5 2012.90
#Mann=3,-1,0
  4847.6    0.07       0  4994.3    0.07       0  4998.3    0.07       0
Bank Sta=4994.3,4998.3
Exp/Cntr=0.3,0.1

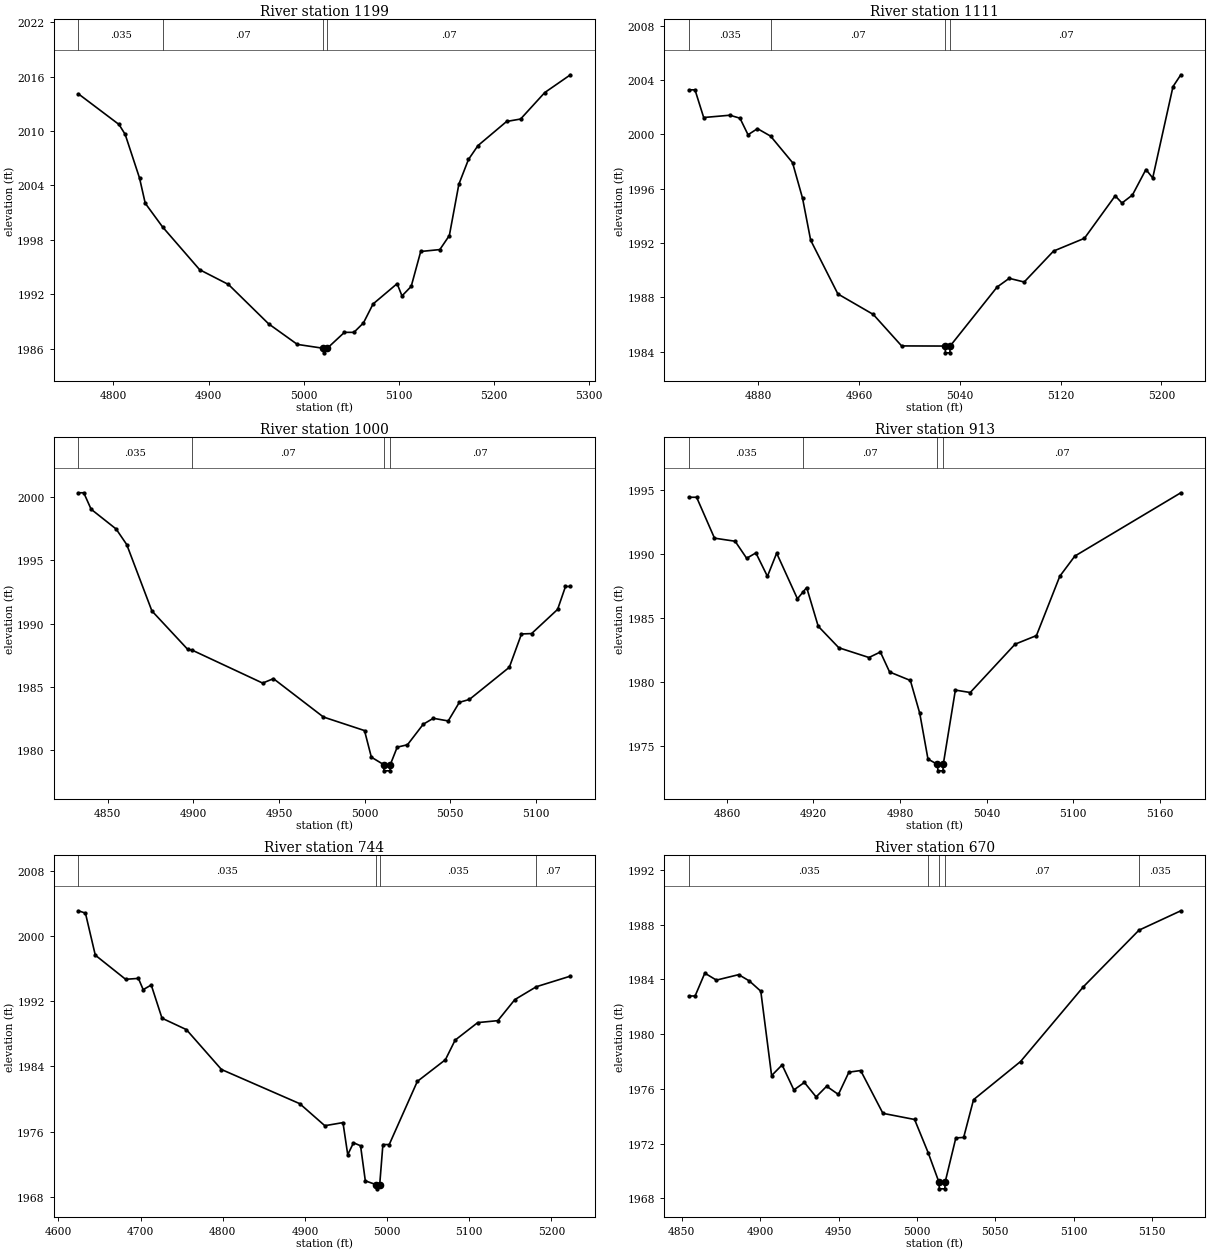
Type RM Length L Ch R = 1,1199,88,88,88
BEGIN DESCRIPTION:
Sweetwater Creek Trib 29 4074
END DESCRIPTION:
XS GIS Cut Line= 3
      1406167.13      6877003.63      1406037.63      6876805.37
      1405758.08      6876827.07
#Sta/Elev= 30
  4763.2 2014.10  4805.8 2010.73  4812.3 2009.64  4827.4 2004.82  4833.4 2002.04
  4851.6 1999.43  4890.6 1994.71  4920.9 1993.08  4963.1 1988.74  4993.3 1986.47
  5020.7 1986.04  5021.0 1985.54  5024.7 1986.04  5042.8 1987.80  5052.8 1987.80
  5062.8 1988.84  5072.9 1990.93  5098.2 1993.17  5103.3 1991.82  5113.0 1992.87
  5123.0 1996.72  5143.1 1996.93  5153.1 1998.48  5163.1 2004.14  5173.2 2006.87
  5183.2 2008.40  5213.3 2011.06  5228.0 2011.33  5253.4 2014.25  5280.4 2016.21
#Mann=4,-1,0
  4763.2   0.035       0  4851.6    0.07       0  5020.7    0.07       0
  5024.7    0.07       0
Bank Sta=5020.7,5024.7
Exp/Cntr=0.3,0.1

Type RM Length L Ch R = 1,1111,111,111,111
BEGIN DESCRIPTION:
Sweetwater Creek Trib 29 4183
END DESCRIPTION:
XS GIS Cut Line= 3
      1406208.49      6876880.75      1406099.82      6876743.44
      1405899.27      6876664.87
#Sta/Elev= 30
  4824.9 2003.29  4829.8 2003.29  4836.7 2001.25  4857.5 2001.42  4865.5 2001.20
  4871.9 1999.98  4879.4 2000.43  4889.8 1999.88  4907.2 1997.93  4915.2 1995.29
  4921.6 1992.21  4943.2 1988.25  4971.3 1986.74  4993.8 1984.42  5028.3 1984.41
  5028.6 1983.91  5032.1 1983.91  5032.3 1984.41  5069.6 1988.76  5079.2 1989.40
  5091.1 1989.13  5114.4 1991.41  5138.9 1992.35  5163.3 1995.48  5168.7 1994.95
  5177.0 1995.54  5187.7 1997.42  5193.1 1996.80  5209.2 2003.53  5215.4 2004.40
#Mann=4,-1,0
  4824.9   0.035       0  4889.8    0.07       0  5028.3    0.07       0
  5032.3    0.07       0
Bank Sta=5028.3,5032.3
Exp/Cntr=0.3,0.1

Type RM Length L Ch R = 1,1000,87,87,87
BEGIN DESCRIPTION:
Sweetwater Creek Trib 29 278
END DESCRIPTION:
XS GIS Cut Line= 3
      1406255.02      6876788.03      1406156.01      6876653.42
      1406055.04      6876588.03
#Sta/Elev= 30
  4832.9 2000.34  4836.0 2000.34  4840.3 1999.04  4854.9 1997.48  4861.1 1996.25
  4875.8 1991.01  4896.6 1987.99  4899.5 1987.90  4940.5 1985.31  4946.8 1985.66
  4976.0 1982.63  5000.0 1981.56  5004.0 1979.46  5011.1 1978.88  5011.4 1978.38
  5014.9 1978.38  5015.1 1978.88  5019.1 1980.25  5025.1 1980.44  5034.3 1982.06
  5040.2 1982.53  5048.9 1982.32  5055.4 1983.79  5061.3 1984.02  5084.6 1986.56
  5091.7 1989.19  5097.6 1989.22  5112.8 1991.13  5117.4 1992.94  5120.3 1992.94
#Mann=4,-1,0
  4832.9   0.035       0  4899.5    0.07       0  5011.1    0.07       0
  5015.1    0.07       0
Bank Sta=5011.1,5015.1
Exp/Cntr=0.3,0.1

Type RM Length L Ch R = 1,913,169,169,169
BEGIN DESCRIPTION:
Sweetwater Creek Trib 29 4182
END DESCRIPTION:
XS GIS Cut Line= 3
      1406307.42      6876711.44      1406202.76      6876582.07
      1406033.98      6876536.99
#Sta/Elev= 30
  4833.6 1994.42  4839.0 1994.42  4851.4 1991.23  4865.7 1990.99  4873.7 1989.66
  4880.1 1990.08  4888.1 1988.25  4894.5 1990.06  4908.9 1986.50  4913.0 1987.06
  4915.3 1987.38  4923.3 1984.36  4937.6 1982.68  4958.5 1981.92  4966.4 1982.35
  4972.8 1980.79  4987.2 1980.13  4993.7 1977.57  4999.4 1974.00  5006.0 1973.58
  5006.3 1973.08  5009.8 1973.08  5010.0 1973.58  5018.4 1979.38  5028.7 1979.19
  5059.8 1982.96  5074.6 1983.63  5090.8 1988.26  5101.2 1989.83  5174.7 1994.77
#Mann=4,-1,0
  4833.6   0.035       0  4913.0    0.07       0  5006.0    0.07       0
  5010.0    0.07       0
Bank Sta=5006,5010
Exp/Cntr=0.3,0.1

Type RM Length L Ch R = 1,744,74,74,74
BEGIN DESCRIPTION:
Sweetwater Creek Trib 29 3986
END DESCRIPTION:
XS GIS Cut Line= 3
      1406397.70      6876735.31      1406204.79      6876412.91
      1405989.82      6876472.96
#Sta/Elev= 30
  4624.3 2003.07  4632.8 2002.78  4644.8 1997.63  4681.7 1994.67  4697.3 1994.78
  4703.1 1993.40  4712.9 1993.97  4726.0 1989.90  4755.7 1988.50  4798.4 1983.61
  4893.7 1979.42  4924.2 1976.72  4946.3 1977.10  4952.1 1973.16  4959.1 1974.63
  4967.7 1974.26  4973.5 1969.96  4987.0 1969.48  4987.3 1968.98  4991.0 1969.48
  4994.9 1974.41  5002.6 1974.41  5036.8 1982.15  5071.0 1984.81  5082.8 1987.21
  5110.3 1989.36  5134.8 1989.60  5155.5 1992.18  5181.7 1993.76  5223.2 1995.06
#Mann=4,-1,0
  4624.3   0.035       0  4987.0   0.035       0  4991.0   0.035       0
  5181.7    0.07       0
Bank Sta=4987,4991
Exp/Cntr=0.3,0.1

Type RM Length L Ch R = 1,670,202,202,202
BEGIN DESCRIPTION:
Sweetwater Creek Trib 29 4181
END DESCRIPTION:
XS GIS Cut Line= 3
      1406349.09      6876448.43      1406240.98      6876351.05
      1406073.07      6876362.52
#Sta/Elev= 30
  4854.5 1982.79  4858.5 1982.79  4864.7 1984.46  4872.1 1983.95  4886.3 1984.35
  4893.1 1983.89  4900.4 1983.14  4907.3 1976.97  4914.0 1977.75  4921.5 1975.92
  4928.2 1976.47  4935.7 1975.41  4942.4 1976.19  4949.9 1975.59  4956.6 1977.22
  4964.1 1977.34  4978.3 1974.21  4998.5 1973.76  5007.2 1971.32  5014.0 1969.19
  5014.3 1968.69  5017.8 1968.69  5018.0 1969.19  5024.8 1972.41  5029.8 1972.45
  5036.1 1975.21  5066.1 1978.00  5106.2 1983.47  5141.6 1987.60  5168.3 1989.02
#Mann=5,-1,0
  4854.5   0.035       0  5007.2    0.07       0  5014.0   0.035       0
  5018.0    0.07       0  5141.6   0.035       0
Bank Sta=5014,5018
Exp/Cntr=0.3,0.1

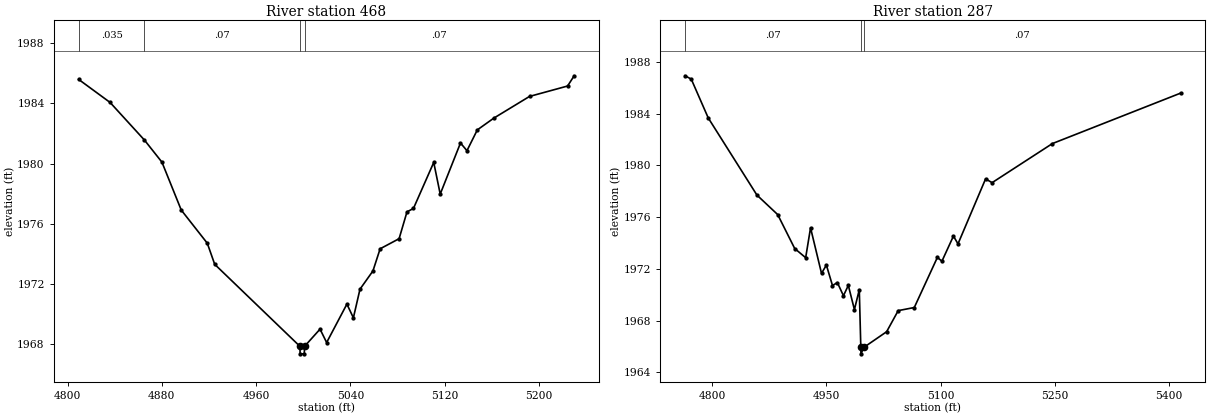
Type RM Length L Ch R = 1,468,181,181,181
BEGIN DESCRIPTION:
Sweetwater Creek Trib 29 4180
END DESCRIPTION:
XS GIS Cut Line= 3
      1406487.15      6876263.57      1406318.51      6876174.74
      1406110.75      6876273.40
#Sta/Elev= 30
  4809.4 1985.59  4836.1 1984.06  4865.3 1981.56  4880.1 1980.10  4896.5 1976.92
  4918.6 1974.72  4924.9 1973.32  4997.2 1967.88  4997.4 1967.38  5000.9 1967.38
  5001.2 1967.88  5014.3 1969.02  5019.9 1968.13  5037.1 1970.68  5042.6 1969.77
  5048.2 1971.67  5059.2 1972.88  5065.3 1974.35  5081.4 1975.02  5088.1 1976.80
  5093.6 1977.03  5110.8 1980.08  5116.3 1977.98  5133.5 1981.37  5139.0 1980.86
  5147.8 1982.24  5161.8 1983.02  5192.1 1984.46  5224.4 1985.15  5230.0 1985.83
#Mann=4,-1,0
  4809.4   0.035       0  4865.3    0.07       0  4997.2    0.07       0
  5001.2    0.07       0
Bank Sta=4997.2,5001.2
Exp/Cntr=0.3,0.1

Type RM Length L Ch R = 1,287,0,0,0
BEGIN DESCRIPTION:
Sweetwater Creek Trib 29 3990
END DESCRIPTION:
XS GIS Cut Line= 3
      1406588.83      6876175.98      1406405.80      6876027.95
      1406057.25      6876253.57
#Sta/Elev= 30
  4764.6 1986.93  4772.7 1986.67  4795.0 1983.67  4858.9 1977.71  4886.2 1976.20
  4908.5 1973.58  4922.9 1972.87  4929.3 1975.18  4943.7 1971.66  4950.1 1972.30
  4958.1 1970.72  4964.5 1970.95  4972.5 1969.93  4978.9 1970.73  4986.9 1968.86
  4993.3 1970.40  4995.3 1965.94  4995.5 1965.44  4999.3 1965.94  5029.2 1967.15
  5044.4 1968.78  5065.5 1969.02  5095.8 1972.89  5101.8 1972.60  5116.9 1974.54
  5122.9 1973.94  5159.1 1978.96  5167.7 1978.67  5246.8 1981.69  5415.2 1985.59
#Mann=3,-1,0
  4764.6    0.07       0  4995.3    0.07       0  4999.3    0.07       0
Bank Sta=4995.3,4999.3
Exp/Cntr=0.3,0.1

Chan Stop Cuts=-1