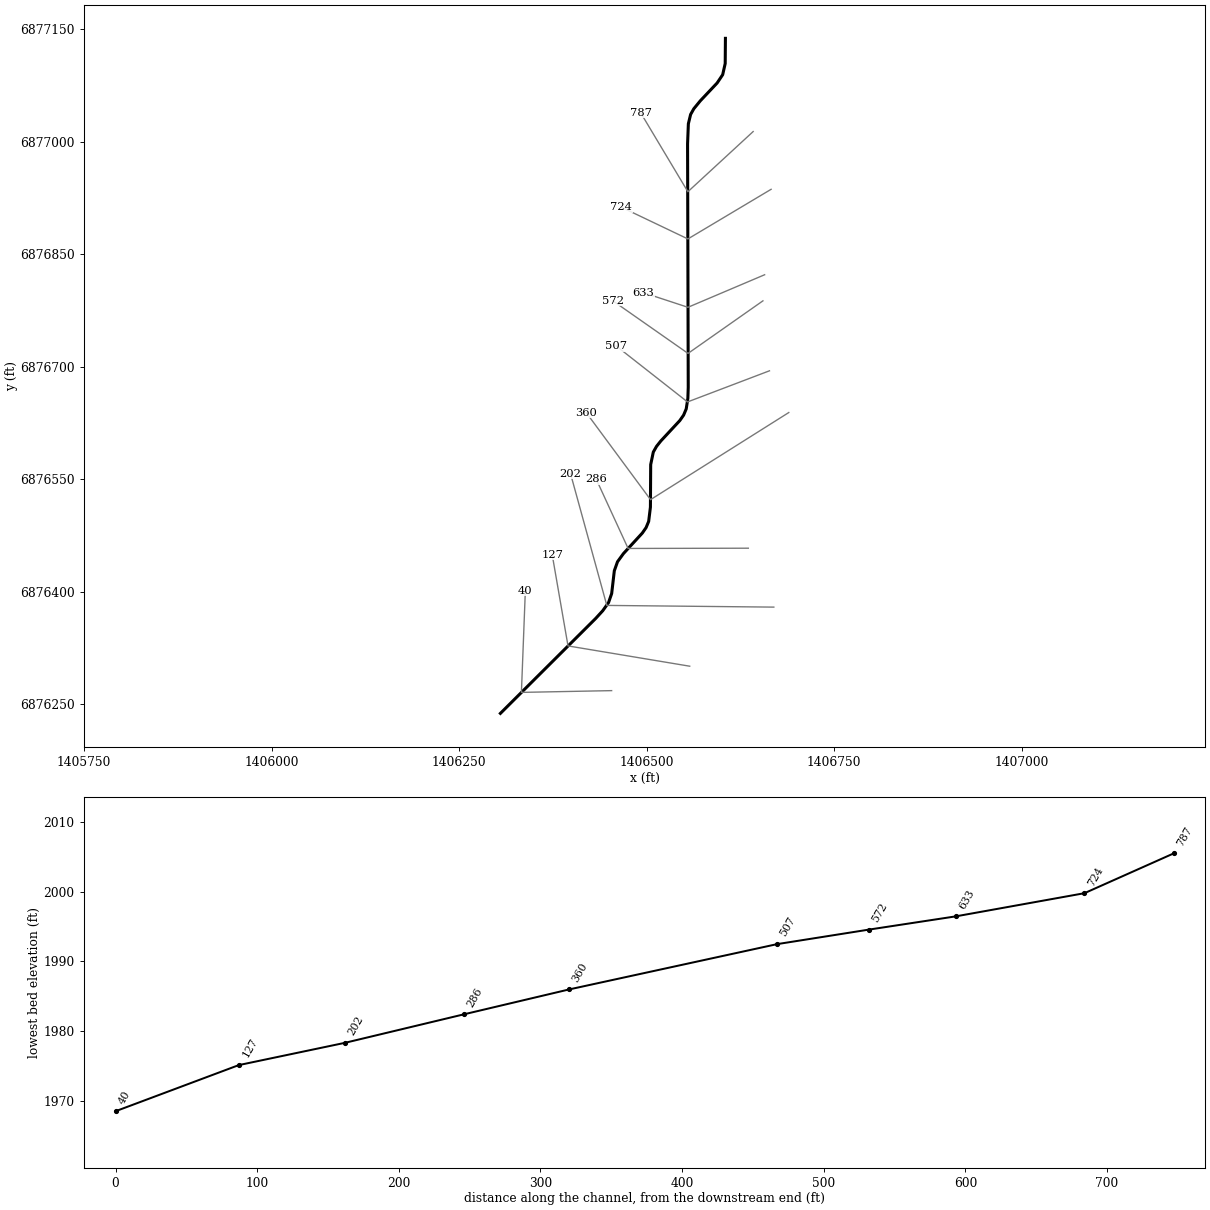
--- Sweetwater Creek Trib 29T.prj (project) ---

Proj Title=Sweetwater Creek Trib 29T Base Level Engineering
Current Plan=p01
Default Exp/Contr=0.3,0.1
English Units
Geom File=g01
Flow File=f01
Plan File=p01
BEGIN DESCRIPTION:
Sweetwater Creek Trib 29T
END DESCRIPTION:

--- Sweetwater Creek Trib 29T.p01 (plan) ---

Plan Title=Multiple Run
Short Identifier=Multiple
Geom File=g01
Flow File=f01
Subcritical Flow
K Sum by GR= 0
Std Step Tol= 0.01
Critical Tol= 0.01
Num of Std Step Trials= 20
Max Error Tol= 0.3
Flow Tol Ratio= 0.001
Split Flow NTrial= 30
Split Flow Tol= 0.02
Split Flow Ratio= 0.02
Log Output Level= 0
Friction Slope Method= 1
Unsteady Friction Slope Method= 2
Unsteady Bridges Friction Slope Method= 1
Parabolic Critical Depth
Global Vel Dist=  1 , 1 , 1
Global Log Level= 0
CheckData=True
Encroach Param= -1, 0, 0, 0
BEGIN DESCRIPTION:
Multiple Run
END DESCRIPTION:

--- Sweetwater Creek Trib 29T.f01 (steady flow) ---

Flow Title=Multiple
Number of Profiles=7
Profile Names=10-year,25-year,50-year,1pct_min,100-year,1pct_plu,500-year
River Rch & RM= Sweetwater Creek,Reach-1,787
      17      20      21      12      23      46      28
Boundary for River Rch & Prof#=Sweetwater Creek,Reach-1,1
Up Type=0
Dn Type=3
Dn Slope=0.005
Boundary for River Rch & Prof#=Sweetwater Creek,Reach-1,2
Up Type=0
Dn Type=3
Dn Slope=0.005
Boundary for River Rch & Prof#=Sweetwater Creek,Reach-1,3
Up Type=0
Dn Type=3
Dn Slope=0.005
Boundary for River Rch & Prof#=Sweetwater Creek,Reach-1,4
Up Type=0
Dn Type=3
Dn Slope=0.005
Boundary for River Rch & Prof#=Sweetwater Creek,Reach-1,5
Up Type=0
Dn Type=3
Dn Slope=0.005
Boundary for River Rch & Prof#=Sweetwater Creek,Reach-1,6
Up Type=0
Dn Type=3
Dn Slope=0.005
Boundary for River Rch & Prof#=Sweetwater Creek,Reach-1,7
Up Type=0
Dn Type=3
Dn Slope=0.005

--- Sweetwater Creek Trib 29T.g01 (geometry) ---

Geom Title=Existing Conditions

River Reach=Sweetwater Creek,Reach-1
Reach XY= 30
      1406605.00      6877138.00      1406604.72      6877104.46
      1406601.35      6877089.51      1406593.94      6877078.44
      1406571.55      6877054.72      1406562.89      6877044.16
      1406558.60      6877036.51      1406555.60      6877024.11
      1406554.54      6876997.28      1406555.43      6876672.82
      1406554.93      6876658.03      1406552.74      6876643.94
      1406549.26      6876635.66      1406544.15      6876628.35
      1406518.83      6876601.13      1406513.19      6876594.03
      1406508.86      6876586.40      1406505.37      6876569.66
      1406505.01      6876513.00      1406502.67      6876493.97
      1406499.23      6876485.68      1406494.16      6876478.35
      1406469.05      6876451.04      1406461.14      6876440.17
      1406456.88      6876428.13      1406453.35      6876397.78
      1406449.17      6876385.70      1406441.39      6876374.78
      1406432.00      6876364.53      1406305.00      6876238.00

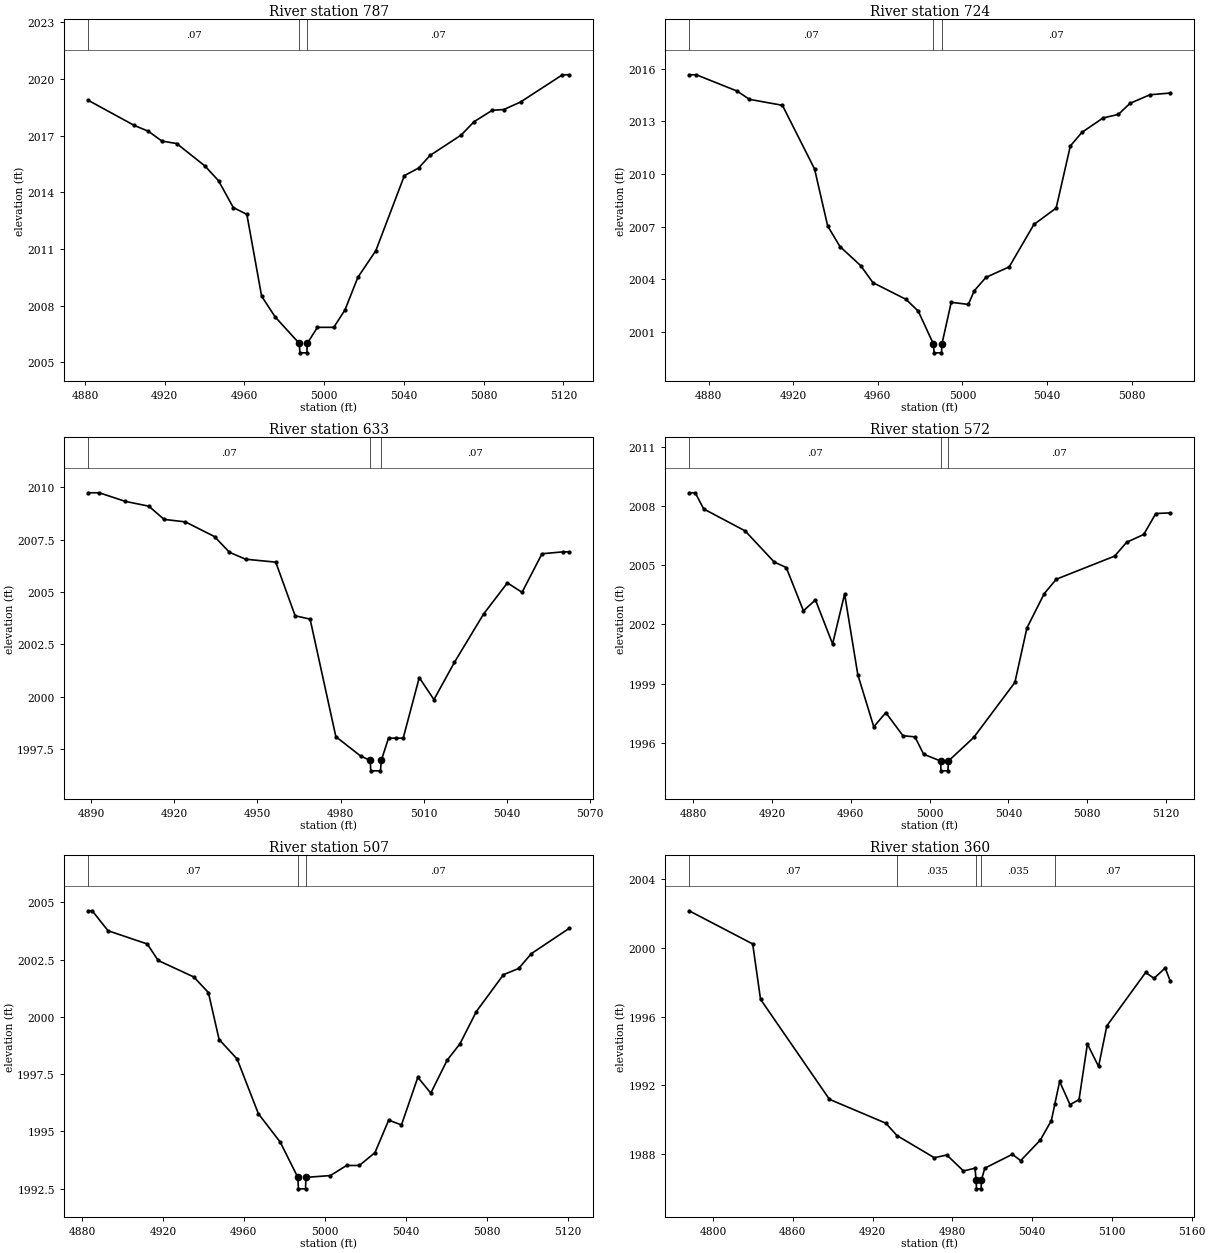
Type RM Length L Ch R = 1,787,63,63,63
BEGIN DESCRIPTION:
Sweetwater Creek Trib 29T 3987
END DESCRIPTION:
XS GIS Cut Line= 3
      1406642.00      6877013.72      1406554.94      6876933.48
      1406491.83      6877039.06
#Sta/Elev= 30
  4881.6 2018.88  4904.7 2017.55  4911.8 2017.24  4918.6 2016.72  4926.0 2016.59
  4940.2 2015.40  4947.0 2014.62  4954.4 2013.20  4961.2 2012.84  4968.6 2008.51
  4975.4 2007.41  4987.5 2006.01  4987.8 2005.51  4991.3 2005.51  4991.5 2006.01
  4996.6 2006.86  5004.8 2006.86  5010.4 2007.78  5016.9 2009.51  5025.9 2010.92
  5040.2 2014.89  5047.3 2015.29  5053.1 2015.96  5068.7 2017.04  5075.2 2017.75
  5084.3 2018.35  5090.1 2018.39  5098.5 2018.79  5119.5 2020.23  5123.0 2020.23
#Mann=3,-1,0
  4881.6    0.07       0  4987.5    0.07       0  4991.5    0.07       0
Bank Sta=4987.5,4991.5
Exp/Cntr=0.3,0.1

Type RM Length L Ch R = 1,724,91,91,91
BEGIN DESCRIPTION:
Sweetwater Creek Trib 29T 4191
END DESCRIPTION:
XS GIS Cut Line= 3
      1406665.94      6876936.73      1406554.97      6876870.54
      1406466.26      6876912.88
#Sta/Elev= 30
  4870.8 2015.65  4874.2 2015.65  4893.5 2014.72  4899.3 2014.25  4914.9 2013.91
  4930.1 2010.28  4936.3 2007.03  4942.1 2005.86  4951.9 2004.77  4957.7 2003.80
  4973.3 2002.85  4979.1 2002.18  4986.3 2000.30  4986.6 1999.80  4990.1 1999.80
  4990.3 2000.30  4994.7 2002.68  5002.8 2002.56  5005.6 2003.34  5011.1 2004.10
  5022.1 2004.70  5033.8 2007.12  5044.3 2008.05  5051.0 2011.59  5056.5 2012.37
  5066.5 2013.19  5073.7 2013.39  5079.2 2014.02  5088.6 2014.51  5098.3 2014.61
#Mann=3,-1,0
  4870.8    0.07       0  4986.3    0.07       0  4990.3    0.07       0
Bank Sta=4986.3,4990.3
Exp/Cntr=0.3,0.1

Type RM Length L Ch R = 1,633,61,61,61
BEGIN DESCRIPTION:
Sweetwater Creek Trib 29T 4192
END DESCRIPTION:
XS GIS Cut Line= 3
      1406657.29      6876822.81      1406555.03      6876779.40
      1406495.56      6876798.95
#Sta/Elev= 30
  4888.9 2009.74  4892.9 2009.74  4902.3 2009.33  4910.8 2009.10  4916.3 2008.47
  4924.0 2008.35  4934.5 2007.65  4939.9 2006.90  4945.7 2006.57  4956.6 2006.43
  4963.6 2003.87  4969.0 2003.71  4978.3 1998.10  4987.3 1997.17  4990.7 1996.97
  4990.9 1996.47  4994.4 1996.47  4994.7 1996.97  4997.3 1998.03  5000.0 1998.03
  5002.6 1998.03  5008.4 2000.92  5013.7 1999.87  5021.1 2001.65  5031.6 2003.95
  5040.2 2005.44  5045.5 2004.99  5052.7 2006.83  5060.2 2006.92  5062.6 2006.92
#Mann=3,-1,0
  4888.9    0.07       0  4990.7    0.07       0  4994.7    0.07       0
Bank Sta=4990.7,4994.7
Exp/Cntr=0.3,0.1

Type RM Length L Ch R = 1,572,65,65,65
BEGIN DESCRIPTION:
Sweetwater Creek Trib 29T 2951
END DESCRIPTION:
XS GIS Cut Line= 3
      1406655.03      6876788.02      1406555.17      6876717.93
      1406455.04      6876787.98
#Sta/Elev= 30
  4878.0 2008.67  4881.1 2008.67  4885.4 2007.85  4906.4 2006.74  4921.2 2005.16
  4927.3 2004.88  4936.0 2002.69  4942.1 2003.24  4950.8 2001.01  4956.9 2003.54
  4963.6 1999.45  4971.7 1996.81  4977.8 1997.53  4986.5 1996.36  4992.6 1996.30
  4997.0 1995.42  5005.6 1995.08  5005.8 1994.58  5009.3 1994.58  5009.6 1995.08
  5022.4 1996.27  5043.3 1999.06  5049.4 2001.82  5058.2 2003.56  5064.3 2004.29
  5093.9 2005.46  5100.0 2006.16  5108.7 2006.56  5114.8 2007.62  5122.2 2007.65
#Mann=3,-1,0
  4878.0    0.07       0  5005.6    0.07       0  5009.6    0.07       0
Bank Sta=5005.6,5009.6
Exp/Cntr=0.3,0.1

Type RM Length L Ch R = 1,507,147,147,147
BEGIN DESCRIPTION:
Sweetwater Creek Trib 29T 4190
END DESCRIPTION:
XS GIS Cut Line= 3
      1406663.75      6876694.75      1406554.48      6876653.22
      1406459.38      6876727.87
#Sta/Elev= 30
  4883.1 2004.63  4885.1 2004.63  4892.9 2003.76  4912.3 2003.18  4917.7 2002.46
  4935.3 2001.74  4942.5 2001.06  4947.8 1999.01  4956.7 1998.16  4967.2 1995.77
  4978.0 1994.53  4986.7 1992.99  4987.0 1992.49  4990.5 1992.49  4990.7 1992.99
  5002.8 1993.07  5010.8 1993.51  5017.1 1993.51  5024.8 1994.07  5031.6 1995.49
  5037.9 1995.28  5046.0 1997.36  5052.4 1996.67  5060.5 1998.11  5066.8 1998.82
  5074.9 2000.23  5088.3 2001.84  5095.8 2002.11  5102.1 2002.76  5120.9 2003.87
#Mann=3,-1,0
  4883.1    0.07       0  4986.7    0.07       0  4990.7    0.07       0
Bank Sta=4986.7,4990.7
Exp/Cntr=0.3,0.1

Type RM Length L Ch R = 1,360,74,74,74
BEGIN DESCRIPTION:
Sweetwater Creek Trib 29T 3988
END DESCRIPTION:
XS GIS Cut Line= 3
      1406689.51      6876639.11      1406505.16      6876522.94
      1406419.59      6876638.76
#Sta/Elev= 30
  4782.1 2002.16  4829.9 2000.23  4835.8 1997.01  4887.6 1991.19  4930.0 1989.80
  4938.4 1989.08  4966.5 1987.79  4975.9 1987.95  4988.4 1987.02  4997.1 1987.18
  4997.9 1986.48  4998.2 1985.98  5001.7 1985.98  5001.9 1986.48  5004.4 1987.18
  5025.2 1987.99  5031.4 1987.62  5046.1 1988.81  5054.5 1989.95  5057.1 1990.91
  5060.7 1992.23  5068.5 1990.88  5075.3 1991.17  5081.6 1994.41  5090.0 1993.10
  5096.2 1995.46  5125.4 1998.57  5131.7 1998.23  5140.1 1998.83  5144.0 1998.05
#Mann=5,-1,0
  4782.1    0.07       0  4938.4   0.035       0  4997.9   0.035       0
  5001.9   0.035       0  5057.1    0.07       0
Bank Sta=4997.9,5001.9
Exp/Cntr=0.3,0.1

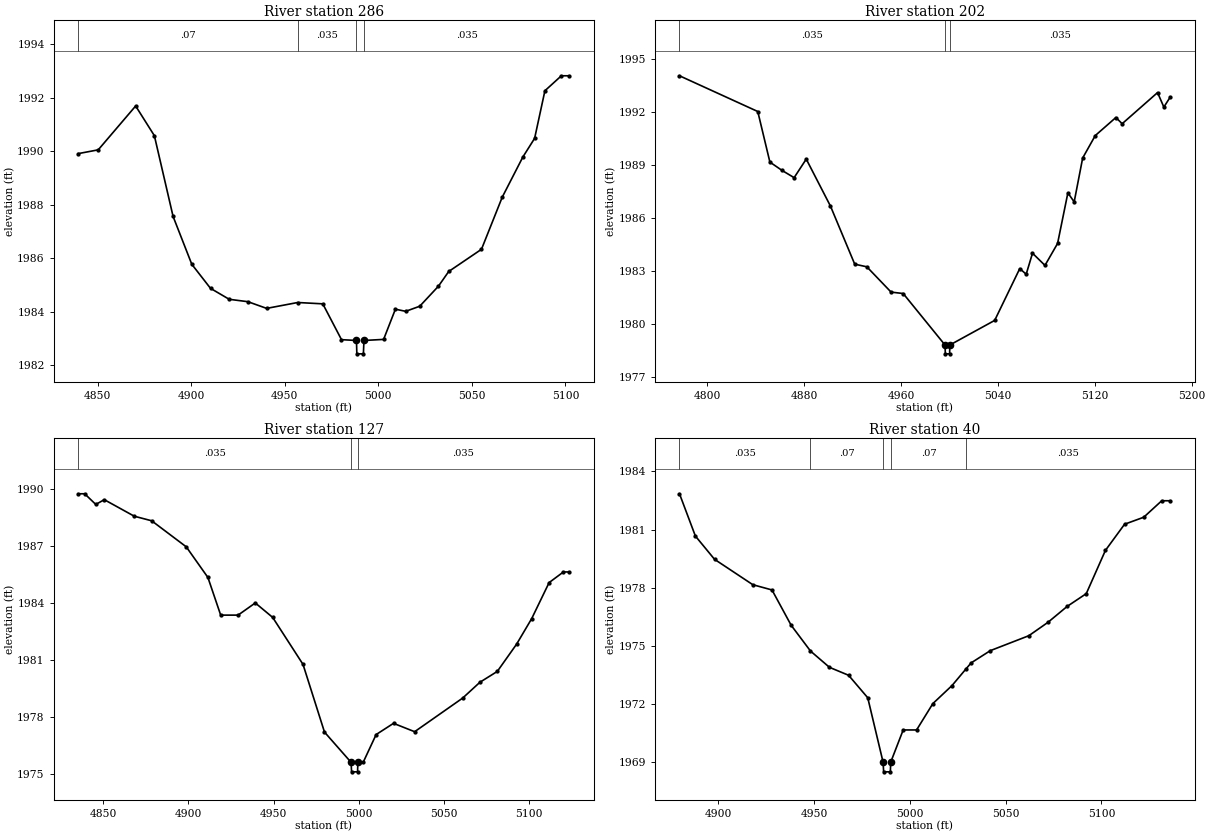
Type RM Length L Ch R = 1,286,84,84,84
BEGIN DESCRIPTION:
Sweetwater Creek Trib 29T 4189
END DESCRIPTION:
XS GIS Cut Line= 3
      1406635.57      6876458.22      1406475.27      6876457.89
      1406432.66      6876550.45
#Sta/Elev= 30
  4839.7 1989.91  4850.3 1990.05  4870.3 1991.69  4880.3 1990.58  4890.3 1987.56
  4900.3 1985.77  4910.3 1984.87  4920.3 1984.46  4930.3 1984.37  4940.3 1984.12
  4956.9 1984.34  4970.3 1984.29  4980.3 1982.95  4988.3 1982.92  4988.5 1982.42
  4992.0 1982.42  4992.3 1982.92  5002.8 1982.96  5009.1 1984.09  5014.6 1984.01
  5022.1 1984.20  5032.1 1984.95  5037.6 1985.50  5055.1 1986.33  5066.2 1988.28
  5077.2 1989.78  5083.5 1990.48  5089.0 1992.26  5097.8 1992.82  5101.9 1992.82
#Mann=4,-1,0
  4839.7    0.07       0  4956.9   0.035       0  4988.3   0.035       0
  4992.3   0.035       0
Bank Sta=4988.3,4992.3
Exp/Cntr=0.3,0.1

Type RM Length L Ch R = 1,202,75,75,75
BEGIN DESCRIPTION:
Sweetwater Creek Trib 29T 3989
END DESCRIPTION:
XS GIS Cut Line= 3
      1406669.55      6876379.67      1406446.87      6876381.94
      1406398.49      6876557.60
#Sta/Elev= 30
  4777.3 1994.05  4841.9 1992.03  4851.9 1989.17  4861.9 1988.70  4871.9 1988.29
  4881.9 1989.34  4901.9 1986.68  4921.9 1983.40  4931.9 1983.25  4951.9 1981.82
  4961.9 1981.74  4996.4 1978.83  4996.7 1978.33  5000.2 1978.33  5000.4 1978.83
  5037.4 1980.22  5058.1 1983.15  5063.4 1982.83  5068.6 1984.02  5078.9 1983.33
  5089.3 1984.57  5097.8 1987.43  5103.0 1986.92  5110.0 1989.40  5120.4 1990.67
  5137.4 1991.69  5142.6 1991.34  5171.8 1993.10  5177.0 1992.28  5182.2 1992.84
#Mann=3,-1,0
  4777.3   0.035       0  4996.4   0.035       0  5000.4   0.035       0
Bank Sta=4996.4,5000.4
Exp/Cntr=0.3,0.1

Type RM Length L Ch R = 1,127,87,87,87
BEGIN DESCRIPTION:
Sweetwater Creek Trib 29T 4188
END DESCRIPTION:
XS GIS Cut Line= 3
      1406557.40      6876300.89      1406395.14      6876327.94
      1406374.07      6876449.53
#Sta/Elev= 30
  4835.5 1989.75  4839.2 1989.75  4845.7 1989.19  4850.7 1989.44  4868.3 1988.57
  4878.5 1988.33  4898.8 1986.96  4911.5 1985.35  4919.0 1983.37  4929.2 1983.37
  4939.3 1984.01  4949.5 1983.25  4967.3 1980.78  4979.9 1977.22  4995.5 1975.63
  4995.8 1975.13  4999.3 1975.13  4999.5 1975.63  5002.6 1975.63  5010.2 1977.09
  5020.4 1977.68  5032.8 1977.24  5061.0 1979.01  5071.1 1979.84  5081.3 1980.41
  5092.6 1981.84  5101.5 1983.19  5111.7 1985.08  5120.1 1985.64  5123.4 1985.64
#Mann=3,-1,0
  4835.5   0.035       0  4995.5   0.035       0  4999.5   0.035       0
Bank Sta=4995.5,4999.5
Exp/Cntr=0.3,0.1

Type RM Length L Ch R = 1,40,0,0,0
BEGIN DESCRIPTION:
Sweetwater Creek Trib 29T 4187
END DESCRIPTION:
XS GIS Cut Line= 3
      1406453.29      6876268.33      1406333.01      6876265.98
      1406338.26      6876401.78
#Sta/Elev= 30
  4879.7 1982.85  4888.0 1980.67  4898.0 1979.47  4918.0 1978.16  4928.0 1977.89
  4938.0 1976.07  4948.1 1974.74  4958.0 1973.90  4968.0 1973.49  4978.0 1972.33
  4986.0 1969.01  4986.3 1968.51  4989.8 1968.51  4990.0 1969.01  4996.5 1970.67
  5003.5 1970.67  5012.0 1972.03  5022.0 1972.96  5029.4 1973.83  5032.0 1974.13
  5042.0 1974.76  5062.1 1975.53  5072.1 1976.22  5082.1 1977.04  5092.1 1977.70
  5102.1 1979.93  5112.1 1981.28  5122.1 1981.64  5131.5 1982.49  5135.9 1982.49
#Mann=5,-1,0
  4879.7   0.035       0  4948.1    0.07       0  4986.0    0.07       0
  4990.0    0.07       0  5029.4   0.035       0
Bank Sta=4986,4990
Exp/Cntr=0.3,0.1

Chan Stop Cuts=-1