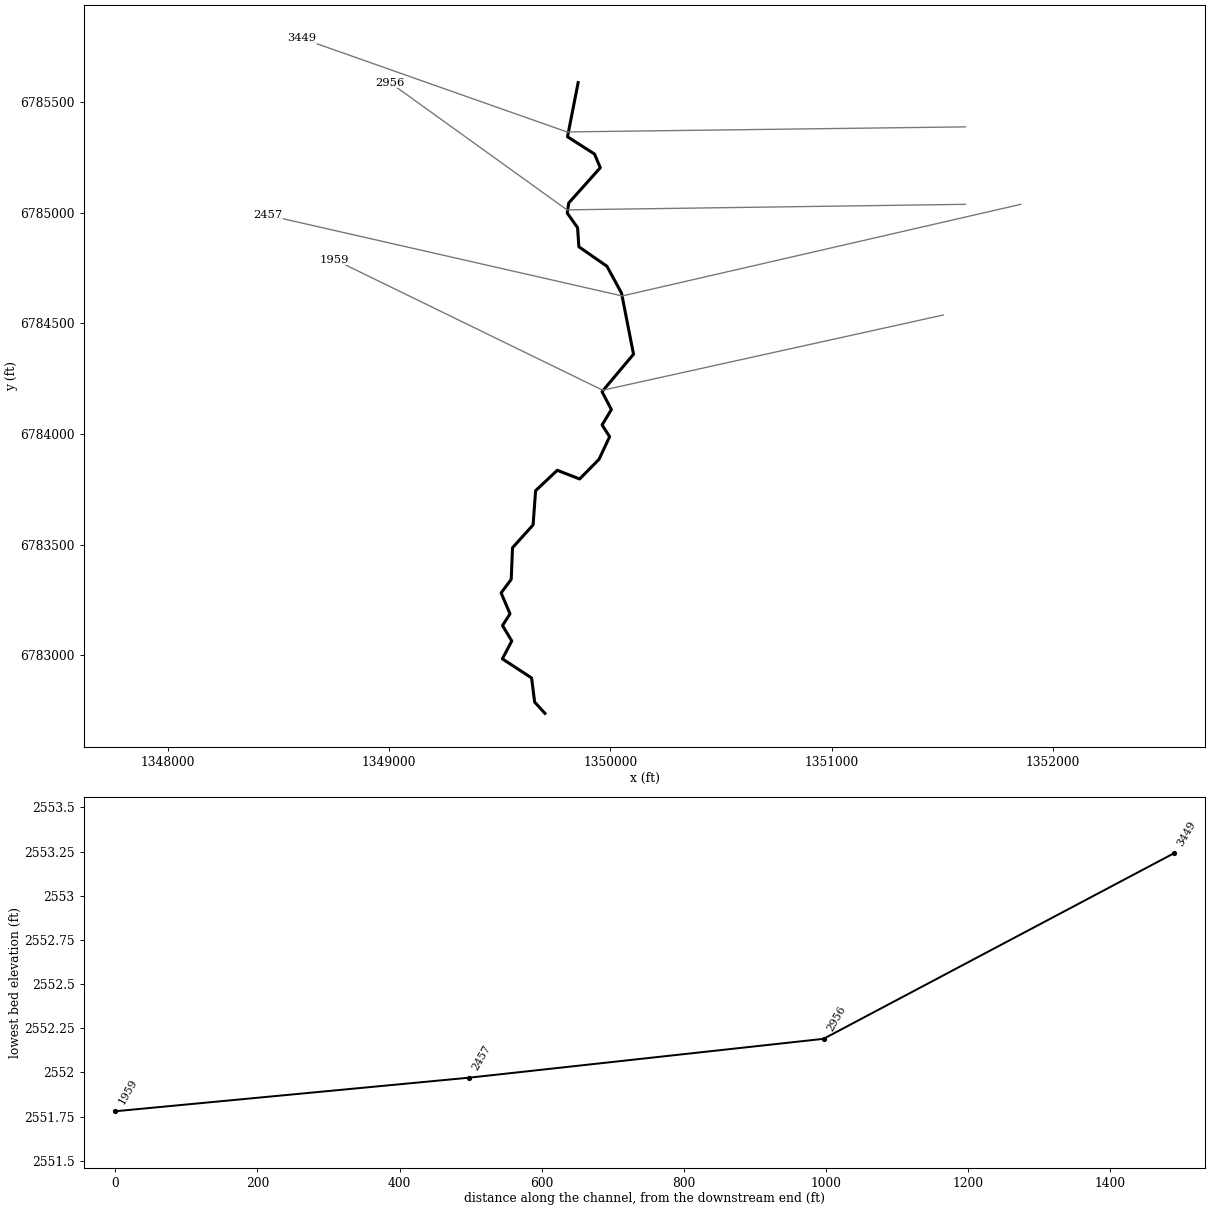
--- Sweetwater Creek Trib2 T.prj (project) ---

Proj Title=Sweetwater Creek Trib2 T Base Level Engineering
Current Plan=p01
Default Exp/Contr=0.3,0.1
English Units
Geom File=g01
Flow File=f01
Plan File=p01
BEGIN DESCRIPTION:
Sweetwater Creek Trib2 T
END DESCRIPTION:

--- Sweetwater Creek Trib2 T.p01 (plan) ---

Plan Title=Multiple Run
Short Identifier=Multiple
Geom File=g01
Flow File=f01
Subcritical Flow
K Sum by GR= 0
Std Step Tol= 0.01
Critical Tol= 0.01
Num of Std Step Trials= 20
Max Error Tol= 0.3
Flow Tol Ratio= 0.001
Split Flow NTrial= 30
Split Flow Tol= 0.02
Split Flow Ratio= 0.02
Log Output Level= 0
Friction Slope Method= 1
Unsteady Friction Slope Method= 2
Unsteady Bridges Friction Slope Method= 1
Parabolic Critical Depth
Global Vel Dist=  1 , 1 , 1
Global Log Level= 0
CheckData=True
Encroach Param= -1, 0, 0, 0
BEGIN DESCRIPTION:
Multiple Run
END DESCRIPTION:

--- Sweetwater Creek Trib2 T.f01 (steady flow) ---

Flow Title=Multiple
Number of Profiles=7
Profile Names=10-year,25-year,50-year,1pct_min,100-year,1pct_plu,500-year
River Rch & RM= Sweetwater Creek,Reach-1,3449
     238     328     402     244     487     973     726
Boundary for River Rch & Prof#=Sweetwater Creek,Reach-1,1
Up Type=0
Dn Type=3
Dn Slope=0.005
Boundary for River Rch & Prof#=Sweetwater Creek,Reach-1,2
Up Type=0
Dn Type=3
Dn Slope=0.005
Boundary for River Rch & Prof#=Sweetwater Creek,Reach-1,3
Up Type=0
Dn Type=3
Dn Slope=0.005
Boundary for River Rch & Prof#=Sweetwater Creek,Reach-1,4
Up Type=0
Dn Type=3
Dn Slope=0.005
Boundary for River Rch & Prof#=Sweetwater Creek,Reach-1,5
Up Type=0
Dn Type=3
Dn Slope=0.005
Boundary for River Rch & Prof#=Sweetwater Creek,Reach-1,6
Up Type=0
Dn Type=3
Dn Slope=0.005
Boundary for River Rch & Prof#=Sweetwater Creek,Reach-1,7
Up Type=0
Dn Type=3
Dn Slope=0.005

--- Sweetwater Creek Trib2 T.g01 (geometry) ---

Geom Title=Existing Conditions

River Reach=Sweetwater Creek,Reach-1
Reach XY= 30
      1349855.00      6785588.00      1349807.00      6785343.30
      1349929.09      6785265.14      1349955.13      6785203.42
      1349812.48      6785044.06      1349805.72      6784998.71
      1349852.47      6784932.36      1349858.16      6784846.34
      1349985.23      6784758.13      1350051.18      6784636.42
      1350105.22      6784360.65      1349962.82      6784191.41
      1350005.20      6784110.80      1349963.32      6784041.23
      1349997.24      6783988.08      1349949.19      6783885.68
      1349861.75      6783797.14      1349760.63      6783836.23
      1349662.81      6783744.21      1349651.44      6783589.47
      1349558.56      6783486.53      1349552.59      6783343.52
      1349506.98      6783282.27      1349547.18      6783187.92
      1349513.32      6783134.77      1349555.20      6783065.20
      1349512.72      6782984.34      1349644.62      6782898.11
      1349658.39      6782789.41      1349705.00      6782738.00

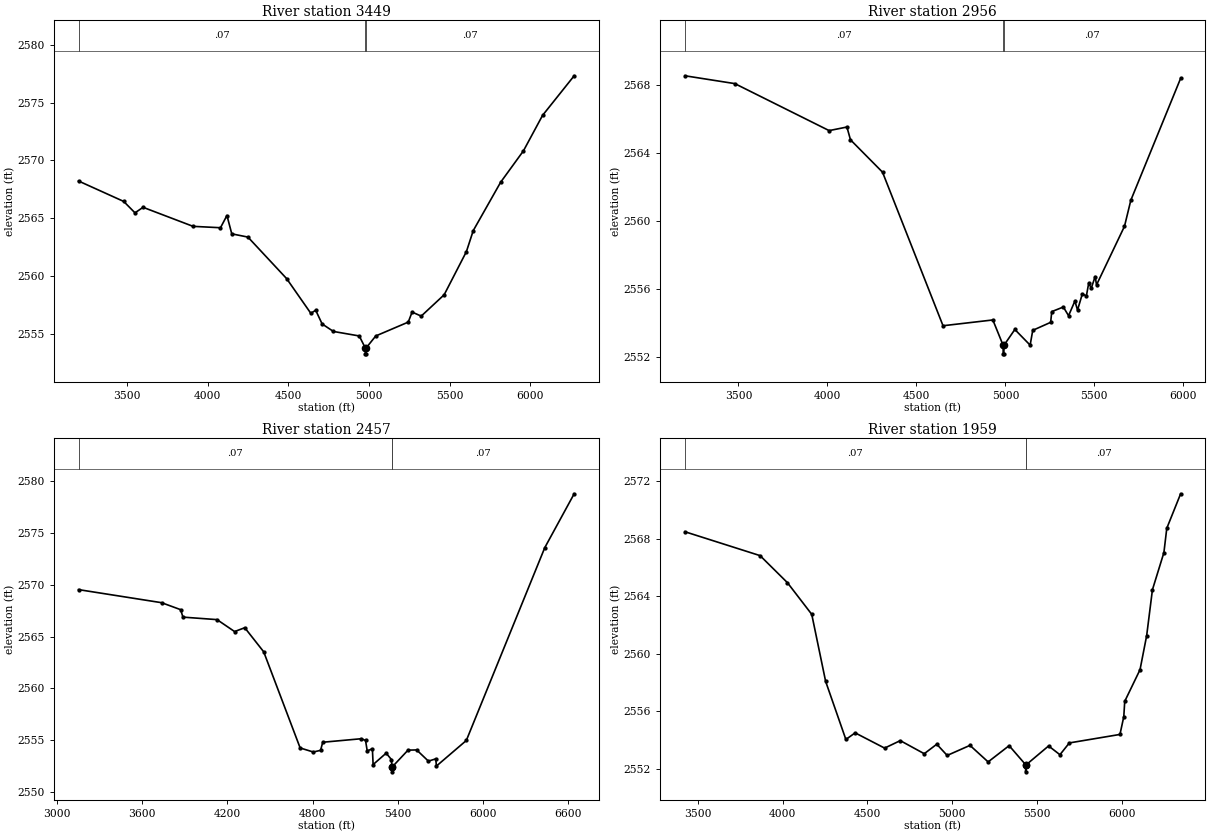
Type RM Length L Ch R = 1,3449,493,493,493
BEGIN DESCRIPTION:
Sweetwater Creek Trib2 T 3.0
END DESCRIPTION:
XS GIS Cut Line= 3
      1351605.03      6785388.00      1349804.38      6785365.13
      1348605.04      6785787.99
#Sta/Elev= 30
  3199.2 2568.22  3479.3 2566.45  3549.3 2565.46  3599.3 2565.94  3909.3 2564.29
  4079.3 2564.17  4119.3 2565.23  4149.3 2563.64  4249.3 2563.36  4489.3 2559.76
  4639.4 2556.75  4669.4 2557.02  4709.4 2555.83  4779.4 2555.18  4939.4 2554.79
  4977.3 2553.74  4977.5 2553.24  4981.2 2553.24  4981.5 2553.74  5041.8 2554.79
  5243.2 2555.99  5267.0 2556.86  5323.6 2556.51  5465.9 2558.36  5603.7 2562.10
  5646.1 2563.92  5815.8 2568.11  5957.5 2570.84  6075.9 2573.91  6271.7 2577.34
#Mann=3,-1,0
  3199.2    0.07       0  4977.3    0.07       0  4981.5    0.07       0
Bank Sta=4977.3,4981.5
Exp/Cntr=0.3,0.1

Type RM Length L Ch R = 1,2956,499,499,499
BEGIN DESCRIPTION:
Sweetwater Creek Trib2 T 2.0
END DESCRIPTION:
XS GIS Cut Line= 3
      1351605.03      6785038.00      1349804.50      6785013.04
      1349004.98      6785588.01
#Sta/Elev= 30
  3199.3 2568.52  3479.4 2568.06  4009.4 2565.30  4109.4 2565.51  4129.4 2564.76
  4309.4 2562.86  4649.5 2553.84  4929.5 2554.18  4987.3 2552.69  4987.6 2552.19
  4991.4 2552.19  4991.7 2552.69  5053.1 2553.62  5139.0 2552.70  5153.7 2553.57
  5254.4 2554.04  5260.5 2554.67  5325.6 2554.94  5355.0 2554.43  5390.6 2555.29
  5405.4 2554.76  5432.4 2555.71  5455.1 2555.59  5468.0 2556.33  5482.7 2556.05
  5504.4 2556.73  5512.2 2556.24  5669.3 2559.68  5704.9 2561.21  5984.8 2568.37
#Mann=3,-1,0
  3199.3    0.07       0  4987.3    0.07       0  4991.7    0.07       0
Bank Sta=4987.3,4991.7
Exp/Cntr=0.3,0.1

Type RM Length L Ch R = 1,2457,498,498,498
BEGIN DESCRIPTION:
Sweetwater Creek Trib2 T 1.0
END DESCRIPTION:
XS GIS Cut Line= 3
      1351855.03      6785038.01      1350054.20      6784624.03
      1348455.00      6784988.00
#Sta/Elev= 30
  3152.2 2569.52  3737.1 2568.26  3870.5 2567.59  3887.3 2566.87  4127.0 2566.63
  4250.5 2565.48  4322.0 2565.85  4455.4 2563.53  4711.9 2554.27  4804.2 2553.88
  4855.5 2554.04  4870.8 2554.82  5142.8 2555.16  5172.0 2554.99  5183.8 2553.99
  5220.2 2554.19  5225.3 2552.67  5317.1 2553.77  5354.4 2553.15  5357.3 2552.47
  5357.6 2551.97  5361.7 2552.47  5470.9 2554.06  5531.7 2554.08  5614.5 2553.00
  5665.8 2553.22  5671.1 2552.53  5881.2 2554.99  6433.6 2573.57  6640.1 2578.75
#Mann=3,-1,0
  3152.2    0.07       0  5357.3    0.07       0  5361.7    0.07       0
Bank Sta=5357.3,5361.7
Exp/Cntr=0.3,0.1

Type RM Length L Ch R = 1,1959,0,0,0
BEGIN DESCRIPTION:
Sweetwater Creek Trib2 T 2406
END DESCRIPTION:
XS GIS Cut Line= 3
      1351505.01      6784538.00      1349966.11      6784198.05
      1348754.96      6784788.02
#Sta/Elev= 30
  3424.0 2568.47  3867.0 2566.81  4028.2 2564.93  4171.6 2562.73  4253.5 2558.07
  4372.9 2554.03  4427.6 2554.49  4601.4 2553.43  4693.8 2553.95  4835.1 2553.04
  4909.0 2553.70  4970.4 2552.92  5104.8 2553.62  5211.9 2552.47  5335.7 2553.60
  5432.8 2552.28  5433.1 2551.78  5437.3 2552.28  5568.5 2553.58  5635.3 2552.97
  5690.8 2553.79  5989.4 2554.38  6012.0 2555.62  6017.5 2556.68  6107.7 2558.88
  6146.9 2561.25  6180.9 2564.44  6248.5 2567.02  6265.5 2568.71  6347.2 2571.11
#Mann=3,-1,0
  3424.0    0.07       0  5432.8    0.07       0  5437.3    0.07       0
Bank Sta=5432.8,5437.3
Exp/Cntr=0.3,0.1

Chan Stop Cuts=-1