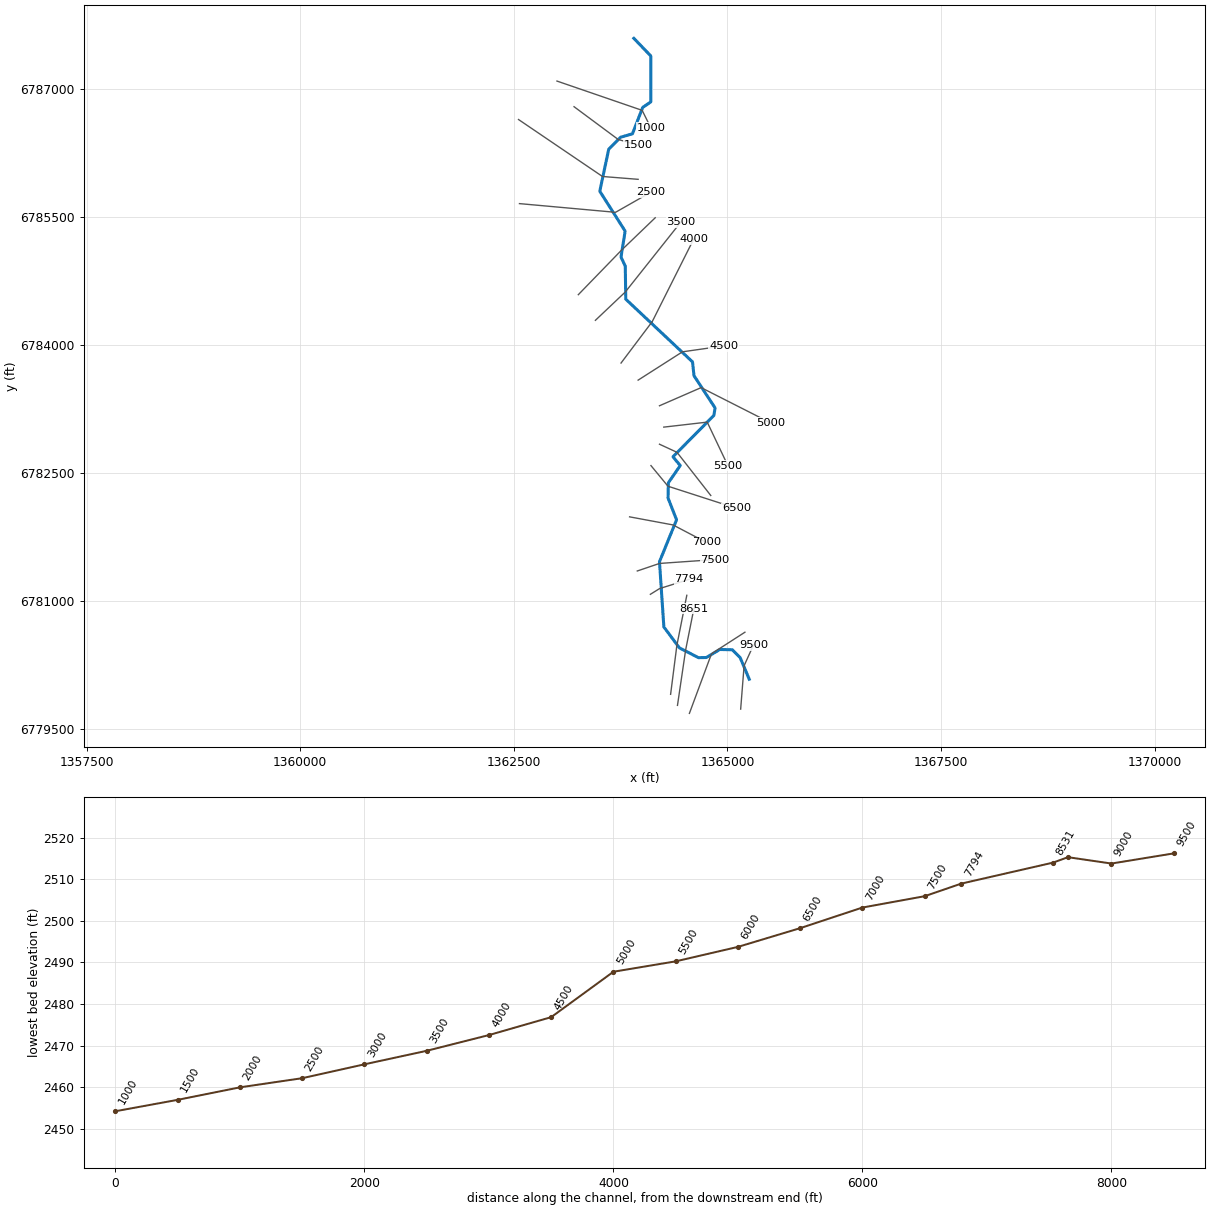
--- Sweetwater Creek Trib 3.prj (project) ---

Proj Title=Sweetwater Creek Trib 3 Base Level Engineering
Current Plan=p01
Default Exp/Contr=0.3,0.1
English Units
Geom File=g01
Flow File=f01
Plan File=p01
BEGIN DESCRIPTION:
Sweetwater Creek Trib 3
END DESCRIPTION:

--- Sweetwater Creek Trib 3.p01 (plan) ---

Plan Title=Multiple Run
Short Identifier=Multiple
Geom File=g01
Flow File=f01
Subcritical Flow
K Sum by GR= 0
Std Step Tol= 0.01
Critical Tol= 0.01
Num of Std Step Trials= 20
Max Error Tol= 0.3
Flow Tol Ratio= 0.001
Split Flow NTrial= 30
Split Flow Tol= 0.02
Split Flow Ratio= 0.02
Log Output Level= 0
Friction Slope Method= 1
Unsteady Friction Slope Method= 2
Unsteady Bridges Friction Slope Method= 1
Parabolic Critical Depth
Global Vel Dist=  1 , 1 , 1
Global Log Level= 0
CheckData=True
Encroach Param= -1, 0, 0, 0
BEGIN DESCRIPTION:
Multiple Run
END DESCRIPTION:

--- Sweetwater Creek Trib 3.f01 (steady flow) ---

Flow Title=Multiple
Number of Profiles=7
Profile Names=10-year,25-year,50-year,1pct_min,100-year,1pct_plu,500-year
River Rch & RM= Sweetwater Creek,Reach-1,9500
     228     315     387     236     472     941     709
River Rch & RM= Sweetwater Creek,Reach-1,7500
     414     598     755     474     946    1887    1503
River Rch & RM= Sweetwater Creek,Reach-1,3500
     610     899    1150     730    1456    2905    2367
Boundary for River Rch & Prof#=Sweetwater Creek,Reach-1,1
Up Type=0
Dn Type=3
Dn Slope=0.005
Boundary for River Rch & Prof#=Sweetwater Creek,Reach-1,2
Up Type=0
Dn Type=3
Dn Slope=0.005
Boundary for River Rch & Prof#=Sweetwater Creek,Reach-1,3
Up Type=0
Dn Type=3
Dn Slope=0.005
Boundary for River Rch & Prof#=Sweetwater Creek,Reach-1,4
Up Type=0
Dn Type=3
Dn Slope=0.005
Boundary for River Rch & Prof#=Sweetwater Creek,Reach-1,5
Up Type=0
Dn Type=3
Dn Slope=0.005
Boundary for River Rch & Prof#=Sweetwater Creek,Reach-1,6
Up Type=0
Dn Type=3
Dn Slope=0.005
Boundary for River Rch & Prof#=Sweetwater Creek,Reach-1,7
Up Type=0
Dn Type=3
Dn Slope=0.005

--- Sweetwater Creek Trib 3.g01 (geometry) ---

Geom Title=Existing Conditions

River Reach=Sweetwater Creek,Reach-1
Reach XY= 30
      1365255.00      6780088.00      1365149.17      6780340.31
      1365057.46      6780432.55      1364910.93      6780435.77
      1364753.42      6780341.67      1364660.97      6780340.14
      1364438.32      6780454.64      1364256.20      6780698.50
      1364204.80      6781463.08      1364404.91      6781953.39
      1364305.07      6782208.03      1364308.55      6782386.53
      1364447.69      6782588.09      1364362.61      6782691.33
      1364841.66      6783174.70      1364855.42      6783263.00
      1364608.76      6783639.56      1364591.63      6783801.32
      1363810.35      6784535.30      1363804.48      6784922.78
      1363754.54      6785027.82      1363802.86      6785332.03
      1363506.19      6785798.50      1363610.83      6786290.30
      1363748.83      6786430.14      1363888.55      6786470.87
      1364008.54      6786779.51      1364103.00      6786843.68
      1364102.94      6787382.15      1363905.00      6787588.00

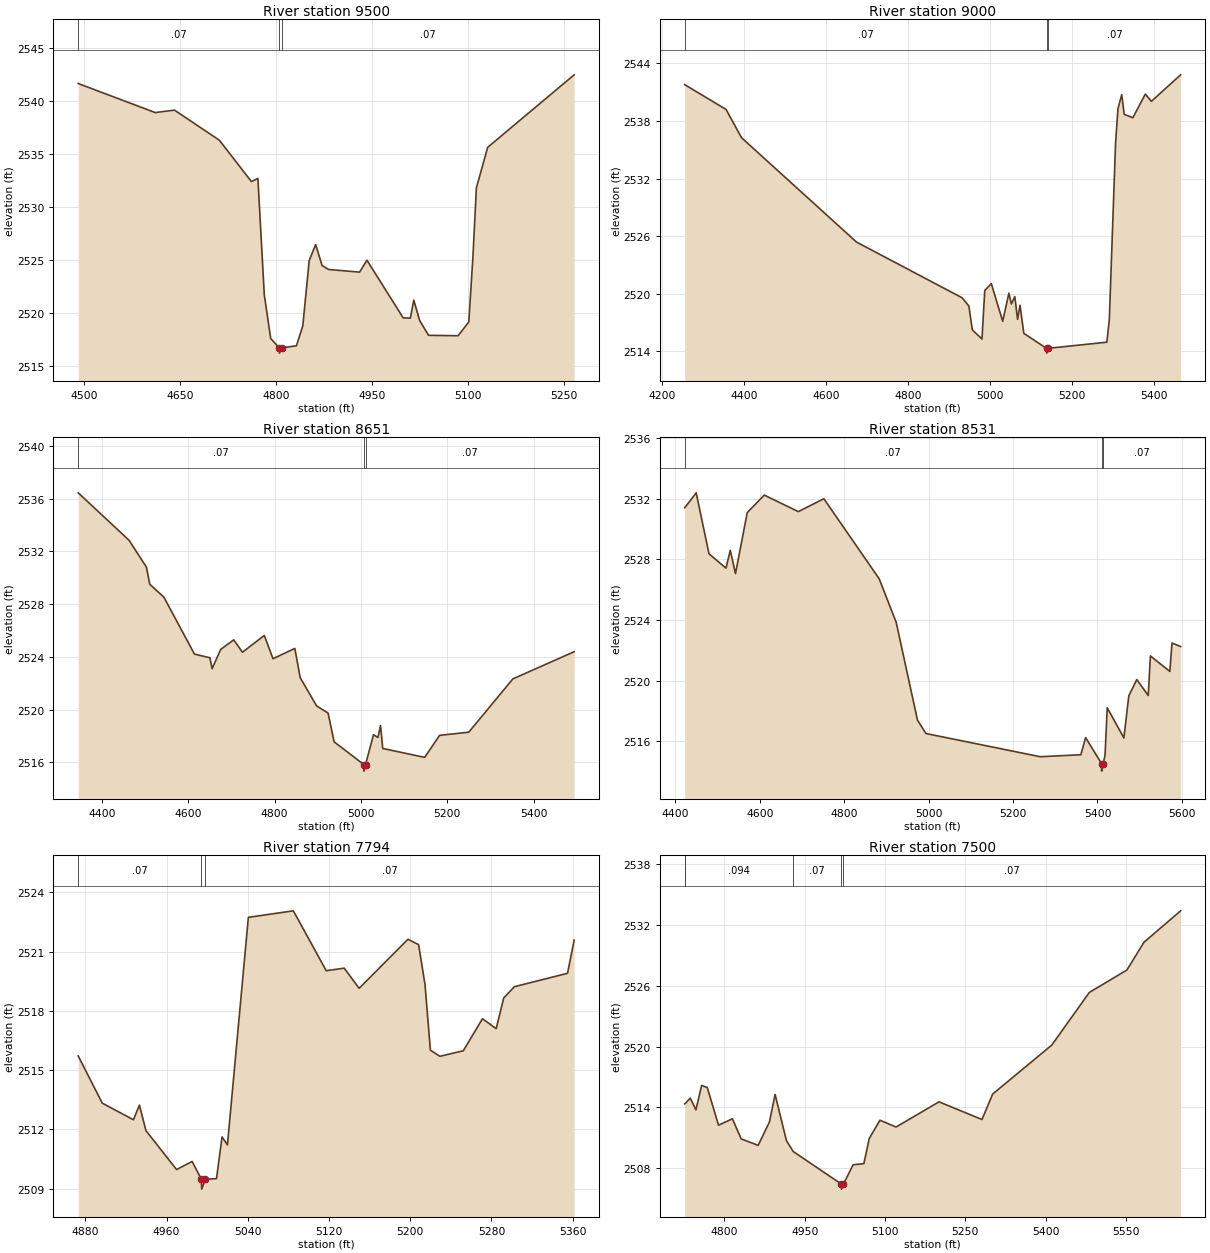
Type RM Length L Ch R = 1,9500,500,500,500
BEGIN DESCRIPTION:
Sweetwater Creek Trib 3 18.0
END DESCRIPTION:
XS GIS Cut Line= 3
      1365155.00      6779738.01      1365195.20      6780245.82
      1365305.00      6780487.99
#Sta/Elev= 30
  4490.6 2541.68  4611.0 2538.94  4641.1 2539.17  4711.3 2536.33  4761.4 2532.43
  4771.5 2532.73  4781.5 2521.75  4791.5 2517.63  4805.0 2516.75  4805.2 2516.25
  4809.0 2516.75  4831.7 2516.94  4841.7 2518.82  4851.7 2524.98  4861.8 2526.49
  4871.8 2524.52  4881.8 2524.14  4930.5 2523.89  4942.0 2525.01  4998.6 2519.58
  5009.8 2519.55  5015.2 2521.25  5024.4 2519.32  5038.3 2517.93  5084.5 2517.89
  5101.2 2519.19  5107.6 2525.27  5113.1 2531.85  5130.7 2535.66  5265.9 2542.50
#Mann=3,-1,0
  4490.6    0.07       0  4805.0    0.07       0  4809.0    0.07       0
Bank Sta=4805,4809
Exp/Cntr=0.3,0.1

Type RM Length L Ch R = 1,9000,349,349,349
BEGIN DESCRIPTION:
Sweetwater Creek Trib 3 17.0
END DESCRIPTION:
XS GIS Cut Line= 3
      1364555.01      6779688.02      1364813.76      6780385.89
      1365204.97      6780637.98
#Sta/Elev= 30
  4255.7 2541.79  4356.7 2539.20  4394.3 2536.26  4674.9 2525.38  4932.3 2519.58
  4948.9 2518.72  4957.3 2516.24  4980.9 2515.28  4987.7 2520.34  5003.7 2521.05
  5031.4 2517.13  5046.6 2520.06  5052.5 2518.93  5061.0 2519.70  5067.7 2517.33
  5073.7 2518.80  5082.9 2515.87  5138.3 2514.31  5138.6 2513.81  5142.3 2514.31
  5285.5 2514.95  5291.5 2517.30  5306.7 2535.66  5312.6 2539.30  5321.8 2540.74
  5327.8 2538.69  5348.9 2538.34  5379.3 2540.80  5394.1 2540.05  5465.4 2542.81
#Mann=3,-1,0
  4255.7    0.07       0  5138.3    0.07       0  5142.3    0.07       0
Bank Sta=5138.3,5142.3
Exp/Cntr=0.3,0.1

Type RM Length L Ch R = 1,8651,120,120,120
BEGIN DESCRIPTION:
Sweetwater Creek Trib 3 16.0
END DESCRIPTION:
XS GIS Cut Line= 3
      1364415.45      6779781.65      1364510.93      6780429.56
      1364607.44      6780913.73
#Sta/Elev= 30
  4345.1 2536.43  4462.7 2532.84  4503.1 2530.80  4510.8 2529.50  4543.6 2528.52
  4614.3 2524.21  4650.2 2523.93  4655.2 2523.10  4675.0 2524.56  4705.3 2525.29
  4725.5 2524.35  4776.1 2525.62  4796.3 2523.86  4846.8 2524.64  4859.2 2522.42
  4897.3 2520.28  4923.8 2519.74  4937.8 2517.56  5006.6 2515.84  5006.9 2515.34
  5010.6 2515.84  5029.0 2518.10  5039.2 2517.89  5045.3 2518.79  5050.4 2517.06
  5147.5 2516.38  5182.0 2518.05  5249.6 2518.29  5351.8 2522.33  5493.7 2524.39
#Mann=3,-1,0
  4345.1    0.07       0  5006.6    0.07       0  5010.6    0.07       0
Bank Sta=5006.6,5010.6
Exp/Cntr=0.3,0.1

Type RM Length L Ch R = 1,8531,737,737,737
BEGIN DESCRIPTION:
Sweetwater Creek Trib 3 15.0
END DESCRIPTION:
XS GIS Cut Line= 3
      1364335.09      6779910.88      1364408.38      6780484.22
      1364524.61      6781069.79
#Sta/Elev= 30
  4422.0 2531.40  4449.3 2532.39  4479.6 2528.37  4519.9 2527.42  4530.0 2528.60
  4542.4 2527.06  4570.3 2531.09  4610.6 2532.24  4691.3 2531.15  4751.8 2532.00
  4882.8 2526.72  4923.2 2523.84  4973.6 2517.39  4993.7 2516.51  5264.5 2514.98
  5360.7 2515.11  5371.9 2516.24  5409.7 2514.53  5409.9 2514.03  5413.7 2514.53
  5418.0 2515.10  5423.1 2518.21  5462.6 2516.22  5474.3 2519.00  5493.2 2520.07
  5520.3 2519.02  5525.4 2521.63  5571.5 2520.61  5576.6 2522.48  5597.0 2522.25
#Mann=3,-1,0
  4422.0    0.07       0  5409.7    0.07       0  5413.7    0.07       0
Bank Sta=5409.7,5413.7
Exp/Cntr=0.3,0.1

Type RM Length L Ch R = 1,7794,294,294,294
BEGIN DESCRIPTION:
Sweetwater Creek Trib 3 14.1
END DESCRIPTION:
XS GIS Cut Line= 3
      1364098.39      6781081.41      1364206.22      6781148.50
      1364551.18      6781256.61
#Sta/Elev= 30
  4873.0 2515.72  4896.7 2513.33  4927.4 2512.49  4933.3 2513.23  4939.7 2511.94
  4969.9 2509.97  4985.2 2510.38  4994.3 2509.48  4994.6 2508.98  4998.3 2509.48
  5009.2 2509.51  5014.7 2511.62  5020.0 2511.22  5040.6 2522.73  5084.9 2523.06
  5117.3 2520.03  5135.0 2520.16  5149.7 2519.14  5197.8 2521.62  5208.3 2521.35
  5214.6 2519.33  5219.9 2516.01  5229.3 2515.70  5252.3 2515.98  5271.2 2517.60
  5284.7 2517.10  5292.1 2518.65  5302.6 2519.22  5355.0 2519.90  5361.5 2521.58
#Mann=3,-1,0
  4873.0    0.07       0  4994.3    0.07       0  4998.3    0.07       0
Bank Sta=4994.3,4998.3
Exp/Cntr=0.3,0.1

Type RM Length L Ch R = 1,7500,500,500,500
BEGIN DESCRIPTION:
Sweetwater Creek Trib 3 14.0
END DESCRIPTION:
XS GIS Cut Line= 3
      1363945.13      6781354.50      1364204.58      6781442.59
      1364855.00      6781488.00
#Sta/Elev= 30
  4726.0 2514.35  4726.5 2514.35  4736.4 2514.92  4747.0 2513.76  4757.6 2516.16
  4768.1 2515.97  4789.2 2512.25  4815.1 2512.88  4831.5 2510.90  4863.2 2510.26
  4884.3 2512.57  4894.8 2515.28  4916.0 2510.73  4928.6 2509.66  5018.5 2506.45
  5018.7 2505.95  5022.5 2506.45  5040.5 2508.35  5060.6 2508.46  5070.6 2510.93
  5090.6 2512.74  5120.7 2512.07  5200.9 2514.55  5281.1 2512.81  5301.1 2515.32
  5411.4 2520.14  5481.6 2525.33  5551.8 2527.54  5583.5 2530.27  5652.0 2533.37
#Mann=5,-1,0
  4726.0    0.07       0  4726.5   0.094       0  4928.6    0.07       0
  5018.5    0.07       0  5022.5    0.07       0
Bank Sta=5018.5,5022.5
Exp/Cntr=0.3,0.1

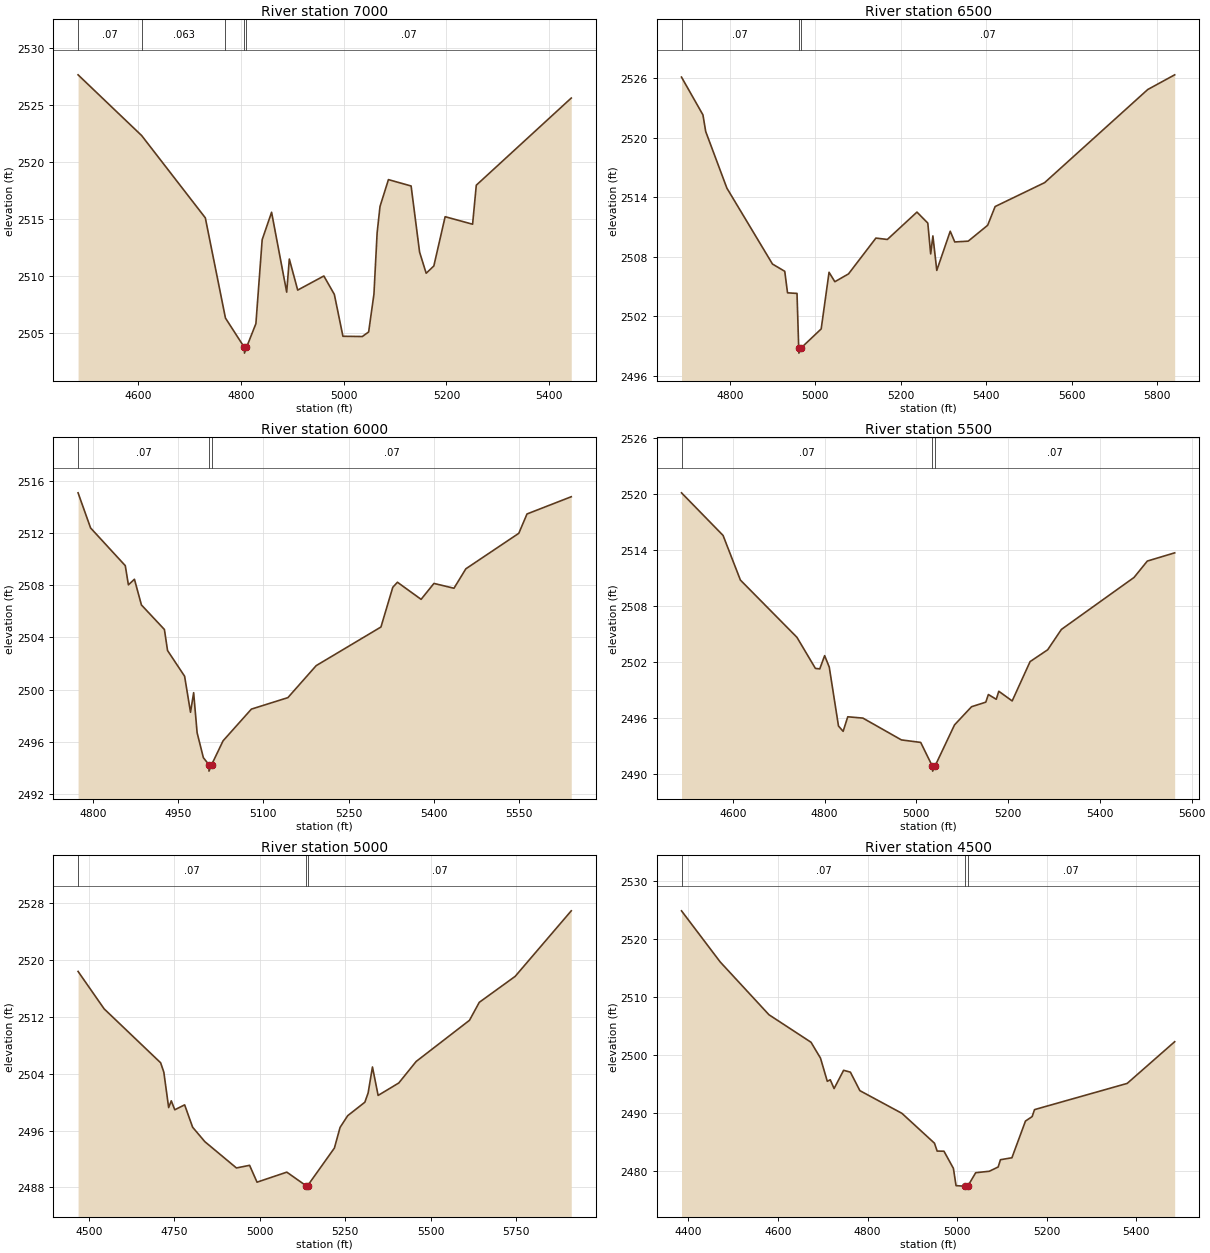
Type RM Length L Ch R = 1,7000,500,500,500
BEGIN DESCRIPTION:
Sweetwater Creek Trib 3 13.0
END DESCRIPTION:
XS GIS Cut Line= 3
      1363854.97      6781988.01      1364362.84      6781893.44
      1364754.99      6781688.00
#Sta/Elev= 30
  4483.4 2527.68  4607.1 2522.34  4730.9 2515.11  4770.1 2506.30  4806.9 2503.72
  4807.1 2503.22  4811.0 2503.72  4829.3 2505.81  4841.5 2513.19  4859.8 2515.60
  4889.2 2508.58  4894.3 2511.49  4910.6 2508.76  4961.5 2510.00  4981.9 2508.38
  4998.6 2504.70  5036.3 2504.68  5048.6 2505.08  5058.9 2508.40  5065.1 2513.79
  5070.7 2516.11  5087.1 2518.47  5131.2 2517.91  5147.7 2512.10  5160.5 2510.24
  5175.4 2510.88  5197.4 2515.21  5250.8 2514.55  5258.0 2517.98  5442.7 2525.64
#Mann=5,-1,0
  4483.4    0.07       0  4607.1   0.063       0  4770.1    0.07       0
  4806.9    0.07       0  4811.0    0.07       0
Bank Sta=4806.9,4811
Exp/Cntr=0.3,0.1

Type RM Length L Ch R = 1,6500,500,500,500
BEGIN DESCRIPTION:
Sweetwater Creek Trib 3 12.0
END DESCRIPTION:
XS GIS Cut Line= 3
      1364104.99      6782588.01      1364304.51      6782346.33
      1365104.96      6782088.01
#Sta/Elev= 30
  4686.6 2526.09  4736.8 2522.28  4743.3 2520.60  4792.8 2514.90  4899.6 2507.24
  4928.3 2506.51  4934.8 2504.34  4957.0 2504.28  4961.0 2498.76  4961.4 2498.26
  4966.0 2498.76  5013.6 2500.70  5032.0 2506.41  5045.6 2505.46  5077.6 2506.25
  5141.7 2509.86  5168.5 2509.72  5237.8 2512.48  5263.2 2511.37  5269.9 2508.26
  5275.1 2510.08  5284.2 2506.60  5315.7 2510.55  5326.3 2509.47  5357.8 2509.55
  5403.3 2511.15  5420.8 2513.04  5536.7 2515.45  5778.1 2524.84  5841.1 2526.32
#Mann=3,-1,0
  4686.6    0.07       0  4961.0    0.07       0  4966.0    0.07       0
Bank Sta=4961,4966
Exp/Cntr=0.3,0.1

Type RM Length L Ch R = 1,6000,500,500,500
BEGIN DESCRIPTION:
Sweetwater Creek Trib 3 11.0
END DESCRIPTION:
XS GIS Cut Line= 3
      1364205.01      6782838.00      1364409.87      6782743.28
      1364804.98      6782238.02
#Sta/Elev= 30
  4774.3 2515.07  4796.3 2512.38  4857.3 2509.49  4862.8 2508.02  4873.4 2508.45
  4885.7 2506.48  4926.1 2504.60  4931.6 2502.99  4961.6 2501.02  4972.0 2498.26
  4977.5 2499.76  4983.6 2496.69  4994.6 2494.78  5004.2 2494.25  5004.5 2493.75
  5009.2 2494.25  5029.2 2496.07  5079.0 2498.50  5143.2 2499.38  5192.9 2501.83
  5306.8 2504.79  5327.6 2507.83  5335.8 2508.22  5377.4 2506.91  5400.0 2508.13
  5435.2 2507.76  5456.1 2509.25  5549.2 2511.97  5563.6 2513.45  5641.4 2514.77
#Mann=3,-1,0
  4774.3    0.07       0  5004.2    0.07       0  5009.2    0.07       0
Bank Sta=5004.2,5009.2
Exp/Cntr=0.3,0.1

Type RM Length L Ch R = 1,5500,500,500,500
BEGIN DESCRIPTION:
Sweetwater Creek Trib 3 10.0
END DESCRIPTION:
XS GIS Cut Line= 3
      1364255.01      6783038.00      1364763.64      6783096.61
      1365005.01      6782587.97
#Sta/Elev= 30
  4488.0 2520.13  4578.6 2515.56  4616.4 2510.77  4739.6 2504.63  4779.9 2501.29
  4789.4 2501.24  4800.0 2502.66  4810.1 2501.43  4830.2 2495.11  4840.3 2494.54
  4850.4 2496.10  4883.4 2495.96  4967.3 2493.62  5009.4 2493.35  5035.1 2490.77
  5035.5 2490.27  5040.2 2490.77  5083.1 2495.23  5120.2 2497.18  5151.3 2497.67
  5156.9 2498.49  5174.1 2497.98  5179.6 2498.84  5208.8 2497.80  5247.8 2502.02
  5286.2 2503.29  5316.0 2505.47  5474.4 2511.05  5503.4 2512.81  5563.0 2513.69
#Mann=3,-1,0
  4488.0    0.07       0  5035.1    0.07       0  5040.2    0.07       0
Bank Sta=5035.1,5040.2
Exp/Cntr=0.3,0.1

Type RM Length L Ch R = 1,5000,500,500,500
BEGIN DESCRIPTION:
Sweetwater Creek Trib 3 9.0
END DESCRIPTION:
XS GIS Cut Line= 3
      1364205.02      6783288.01      1364692.15      6783500.37
      1365505.03      6783087.99
#Sta/Elev= 30
  4468.6 2518.41  4544.9 2513.14  4710.2 2505.55  4719.5 2504.23  4733.6 2499.25
  4741.3 2500.20  4751.5 2498.94  4780.4 2499.63  4803.8 2496.48  4839.5 2494.45
  4931.9 2490.75  4970.4 2491.12  4992.2 2488.75  5079.3 2490.16  5135.1 2488.27
  5135.5 2487.77  5140.4 2488.27  5218.5 2493.55  5235.2 2496.46  5257.5 2498.11
  5307.6 2500.00  5317.2 2501.30  5329.9 2504.96  5346.5 2500.96  5406.9 2502.71
  5457.8 2505.74  5613.7 2511.53  5642.4 2514.06  5747.3 2517.71  5911.5 2526.94
#Mann=3,-1,0
  4468.6    0.07       0  5135.1    0.07       0  5140.4    0.07       0
Bank Sta=5135.1,5140.4
Exp/Cntr=0.3,0.1

Type RM Length L Ch R = 1,4500,500,500,500
BEGIN DESCRIPTION:
Sweetwater Creek Trib 3 8.0
END DESCRIPTION:
XS GIS Cut Line= 3
      1363954.98      6783587.99      1364473.67      6783919.35
      1364955.00      6783988.00
#Sta/Elev= 30
  4384.5 2524.83  4470.8 2516.03  4579.9 2506.91  4673.8 2502.17  4695.0 2499.43
  4710.2 2495.43  4716.8 2495.70  4725.4 2494.18  4746.6 2497.33  4761.8 2497.01
  4783.0 2493.82  4876.9 2489.91  4949.6 2484.76  4955.6 2483.40  4970.8 2483.38
  4991.9 2480.42  4997.8 2477.44  5018.4 2477.34  5018.9 2476.84  5023.9 2477.34
  5041.7 2479.67  5072.1 2479.92  5091.9 2480.66  5097.0 2481.91  5122.6 2482.25
  5152.9 2488.58  5167.8 2489.35  5173.1 2490.55  5380.1 2495.07  5486.2 2502.26
#Mann=3,-1,0
  4384.5    0.07       0  5018.4    0.07       0  5023.9    0.07       0
Bank Sta=5018.4,5023.9
Exp/Cntr=0.3,0.1

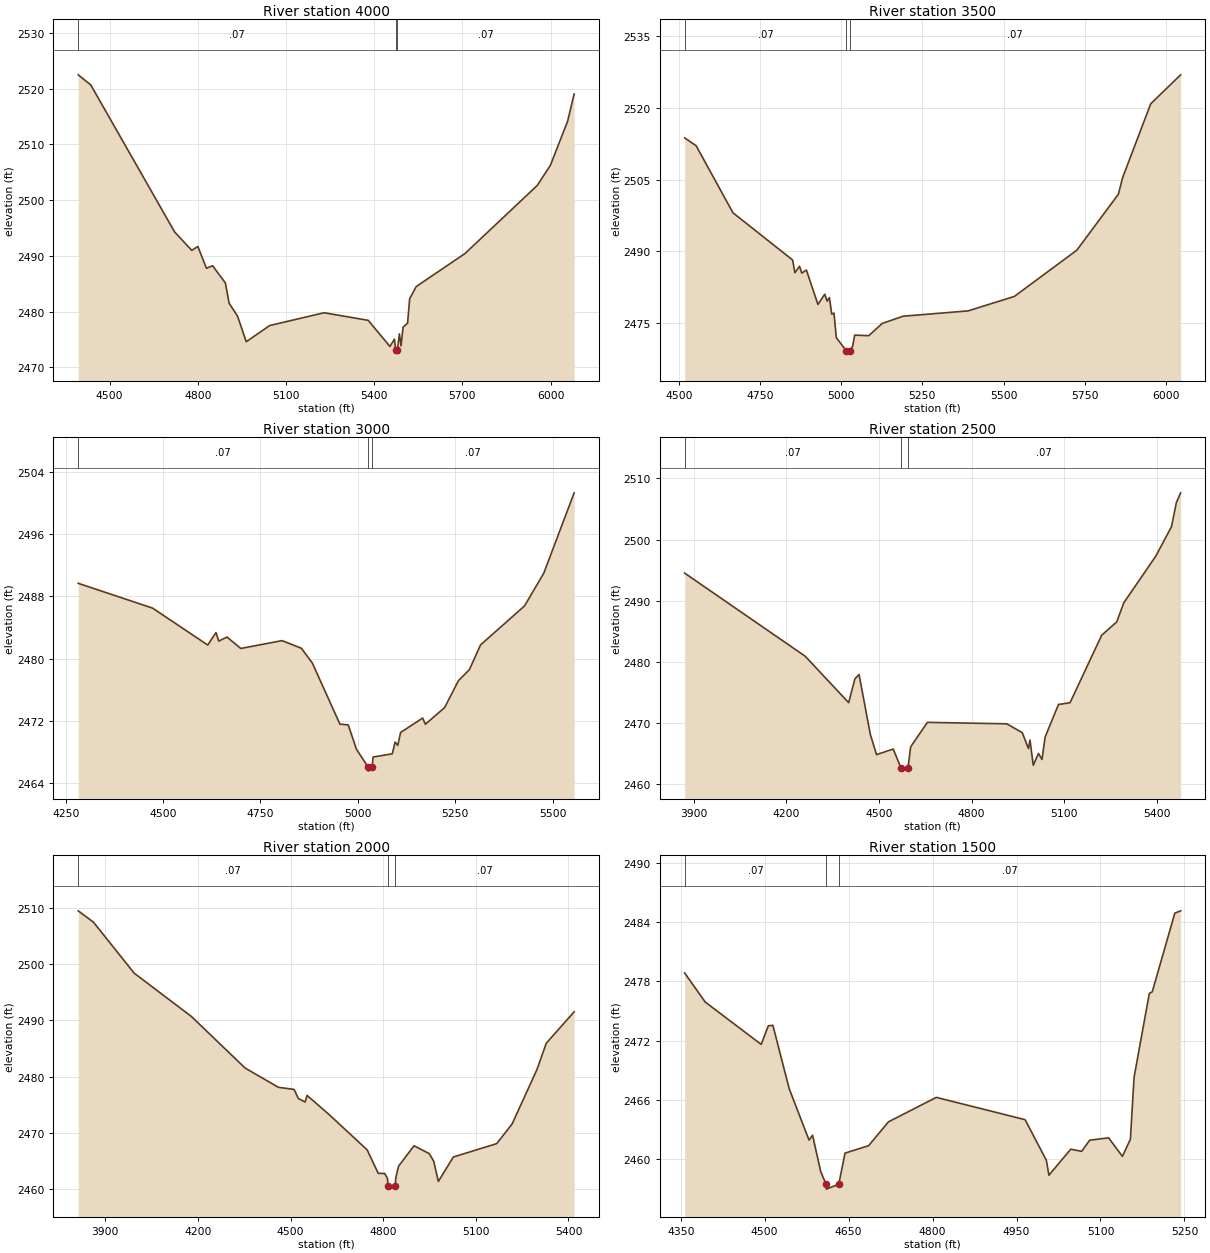
Type RM Length L Ch R = 1,4000,500,500,500
BEGIN DESCRIPTION:
Sweetwater Creek Trib 3 7.0
END DESCRIPTION:
XS GIS Cut Line= 3
      1363754.99      6783787.99      1364120.11      6784272.90
      1364605.01      6785238.03
#Sta/Elev= 30
  4393.0 2522.51  4435.7 2520.70  4721.0 2494.29  4779.3 2490.99  4800.1 2491.68
  4829.2 2487.77  4850.1 2488.22  4893.7 2485.14  4906.3 2481.51  4935.4 2479.13
  4964.6 2474.58  5044.6 2477.49  5229.5 2479.78  5379.5 2478.42  5453.4 2473.73
  5468.8 2475.05  5472.9 2473.03  5473.4 2472.53  5478.5 2473.03  5485.6 2475.99
  5491.2 2473.83  5498.1 2477.20  5513.5 2477.91  5520.5 2482.30  5542.9 2484.49
  5708.9 2490.42  5954.5 2502.64  5999.1 2506.24  6057.7 2514.15  6080.1 2519.07
#Mann=3,-1,0
  4393.0    0.07       0  5472.9    0.07       0  5478.5    0.07       0
Bank Sta=5472.9,5478.5
Exp/Cntr=0.3,0.1

Type RM Length L Ch R = 1,3500,500,500,500
BEGIN DESCRIPTION:
Sweetwater Creek Trib 3 6.0
END DESCRIPTION:
XS GIS Cut Line= 3
      1363454.99      6784287.99      1363804.78      6784619.46
      1364455.02      6785438.03
#Sta/Elev= 30
  4518.1 2513.75  4553.5 2512.10  4666.8 2498.09  4850.4 2488.22  4857.7 2485.56
  4871.9 2486.91  4878.7 2485.47  4892.9 2486.12  4928.5 2478.92  4949.5 2481.06
  4956.8 2479.62  4963.7 2480.35  4971.0 2476.90  4977.9 2477.12  4985.1 2471.97
  5015.9 2469.24  5016.4 2468.74  5025.8 2469.24  5035.3 2470.16  5041.7 2472.50
  5085.0 2472.39  5126.6 2474.95  5190.7 2476.46  5390.9 2477.57  5533.5 2480.60
  5725.8 2490.27  5853.8 2501.98  5866.7 2505.42  5953.3 2520.88  6045.4 2526.94
#Mann=3,-1,0
  4518.1    0.07       0  5015.9    0.07       0  5025.8    0.07       0
Bank Sta=5015.9,5025.8
Exp/Cntr=0.3,0.1

Type RM Length L Ch R = 1,3000,500,500,500
BEGIN DESCRIPTION:
Sweetwater Creek Trib 3 5.0
END DESCRIPTION:
XS GIS Cut Line= 3
      1363254.99      6784587.99      1363754.81      6785103.32
      1364155.00      6785488.00
#Sta/Elev= 30
  4282.1 2489.70  4473.1 2486.50  4614.6 2481.74  4635.7 2483.35  4642.9 2482.25
  4664.0 2482.77  4699.4 2481.30  4805.4 2482.31  4854.9 2481.33  4883.1 2479.42
  4953.9 2471.54  4975.2 2471.45  4996.3 2468.31  5026.7 2465.99  5027.2 2465.49
  5036.6 2465.99  5038.9 2467.31  5088.3 2467.72  5095.5 2469.24  5102.4 2468.80
  5109.6 2470.47  5166.2 2472.33  5173.2 2471.53  5222.6 2473.68  5258.1 2477.15
  5286.4 2478.58  5314.7 2481.75  5427.9 2486.79  5477.3 2491.02  5555.1 2501.36
#Mann=3,-1,0
  4282.1    0.07       0  5026.7    0.07       0  5036.6    0.07       0
Bank Sta=5026.7,5036.6
Exp/Cntr=0.3,0.1

Type RM Length L Ch R = 1,2500,500,500,500
BEGIN DESCRIPTION:
Sweetwater Creek Trib 3 4.0
END DESCRIPTION:
XS GIS Cut Line= 3
      1362566.19      6785653.74      1363690.70      6785552.00
      1364104.99      6785788.00
#Sta/Elev= 30
  3870.9 2494.51  4261.3 2480.92  4401.9 2473.34  4422.0 2477.21  4435.5 2477.94
  4472.2 2468.12  4492.2 2464.85  4546.2 2465.76  4571.3 2462.65  4571.8 2462.15
  4593.9 2462.65  4602.7 2466.13  4656.9 2470.12  4914.0 2469.88  4964.2 2468.43
  4984.0 2465.83  4989.1 2467.23  4999.7 2463.10  5016.5 2465.04  5028.0 2464.06
  5038.1 2467.73  5081.3 2473.04  5118.8 2473.33  5221.1 2484.35  5270.0 2486.54
  5292.7 2489.65  5396.2 2497.27  5447.3 2502.10  5463.1 2506.05  5476.8 2507.63
#Mann=3,-1,0
  3870.9    0.07       0  4571.3    0.07       0  4593.9    0.07       0
Bank Sta=4571.3,4593.9
Exp/Cntr=0.3,0.1

Type RM Length L Ch R = 1,2000,500,500,500
BEGIN DESCRIPTION:
Sweetwater Creek Trib 3 3.0
END DESCRIPTION:
XS GIS Cut Line= 3
      1362555.01      6786637.99      1363537.84      6785971.15
      1363955.03      6785938.00
#Sta/Elev= 30
  3812.3 2509.50  3861.7 2507.48  3993.4 2498.41  4179.1 2490.68  4352.8 2481.51
  4460.6 2478.08  4511.5 2477.70  4525.3 2476.08  4547.4 2475.46  4553.5 2476.64
  4625.3 2473.21  4748.1 2466.94  4784.0 2462.76  4805.0 2462.74  4813.9 2461.85
  4816.0 2460.45  4816.5 2459.95  4838.7 2460.45  4841.0 2462.01  4849.9 2464.04
  4899.9 2467.67  4948.8 2466.29  4963.7 2464.92  4978.7 2461.31  5027.2 2465.67
  5167.7 2468.05  5217.8 2471.57  5298.1 2481.25  5328.2 2485.93  5418.5 2491.52
#Mann=3,-1,0
  3812.3    0.07       0  4816.0    0.07       0  4838.7    0.07       0
Bank Sta=4816,4838.7
Exp/Cntr=0.3,0.1

Type RM Length L Ch R = 1,1500,500,500,500
BEGIN DESCRIPTION:
Sweetwater Creek Trib 3 2.0
END DESCRIPTION:
XS GIS Cut Line= 3
      1363204.98      6786788.02      1363721.20      6786404.82
      1363955.03      6786337.99
#Sta/Elev= 30
  4357.1 2478.85  4393.7 2475.91  4493.8 2471.61  4506.6 2473.50  4514.7 2473.54
  4543.9 2467.11  4579.3 2461.91  4585.6 2462.40  4600.2 2458.71  4609.7 2457.44
  4610.2 2456.94  4632.4 2457.44  4643.6 2460.59  4685.7 2461.34  4721.2 2463.76
  4806.7 2466.24  4965.3 2463.98  5003.3 2459.87  5007.9 2458.35  5046.9 2460.99
  5066.4 2460.77  5080.7 2461.90  5114.5 2462.14  5139.2 2460.26  5153.5 2462.00
  5160.0 2468.26  5187.3 2476.78  5192.5 2476.93  5232.8 2484.91  5243.2 2485.15
#Mann=3,-1,0
  4357.1    0.07       0  4609.7    0.07       0  4632.4    0.07       0
Bank Sta=4609.7,4632.4
Exp/Cntr=0.3,0.1

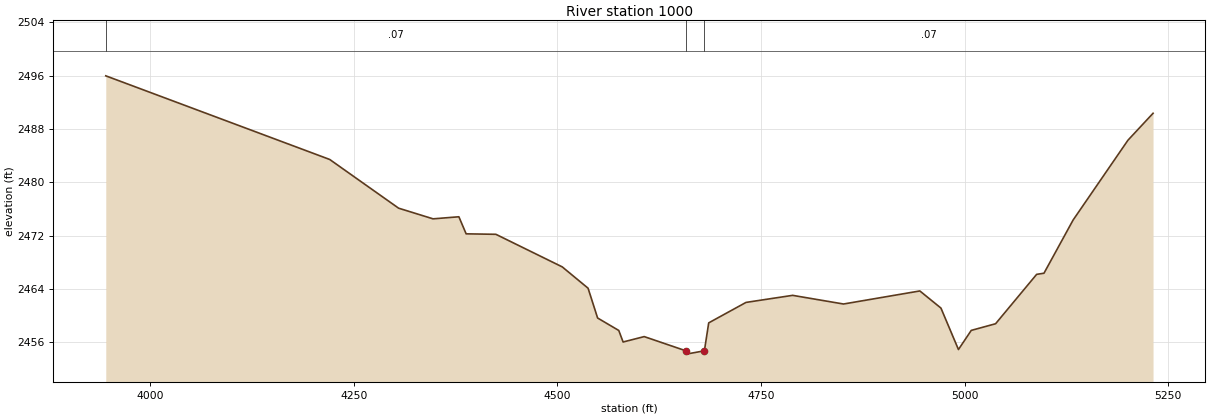
Type RM Length L Ch R = 1,1000,0,0,0
BEGIN DESCRIPTION:
Sweetwater Creek Trib 3 1.0
END DESCRIPTION:
XS GIS Cut Line= 3
      1363005.04      6787087.99      1364002.24      6786745.12
      1364104.99      6786538.01
#Sta/Elev= 30
  3945.5 2495.96  4220.4 2483.41  4305.0 2476.10  4347.3 2474.50  4379.0 2474.81
  4387.9 2472.25  4424.4 2472.18  4505.9 2467.29  4537.6 2464.09  4549.3 2459.62
  4575.3 2457.75  4580.6 2456.02  4606.5 2456.83  4657.6 2454.70  4658.1 2454.20
  4680.4 2454.70  4685.7 2458.89  4731.5 2461.96  4788.7 2463.02  4851.2 2461.72
  4944.9 2463.68  4970.8 2461.11  4992.3 2454.89  5008.0 2457.76  5037.9 2458.76
  5088.3 2466.17  5097.3 2466.34  5133.1 2474.33  5200.4 2486.30  5231.2 2490.34
#Mann=3,-1,0
  3945.5    0.07       0  4657.6    0.07       0  4680.4    0.07       0
Bank Sta=4657.6,4680.4
Exp/Cntr=0.3,0.1

Chan Stop Cuts=-1