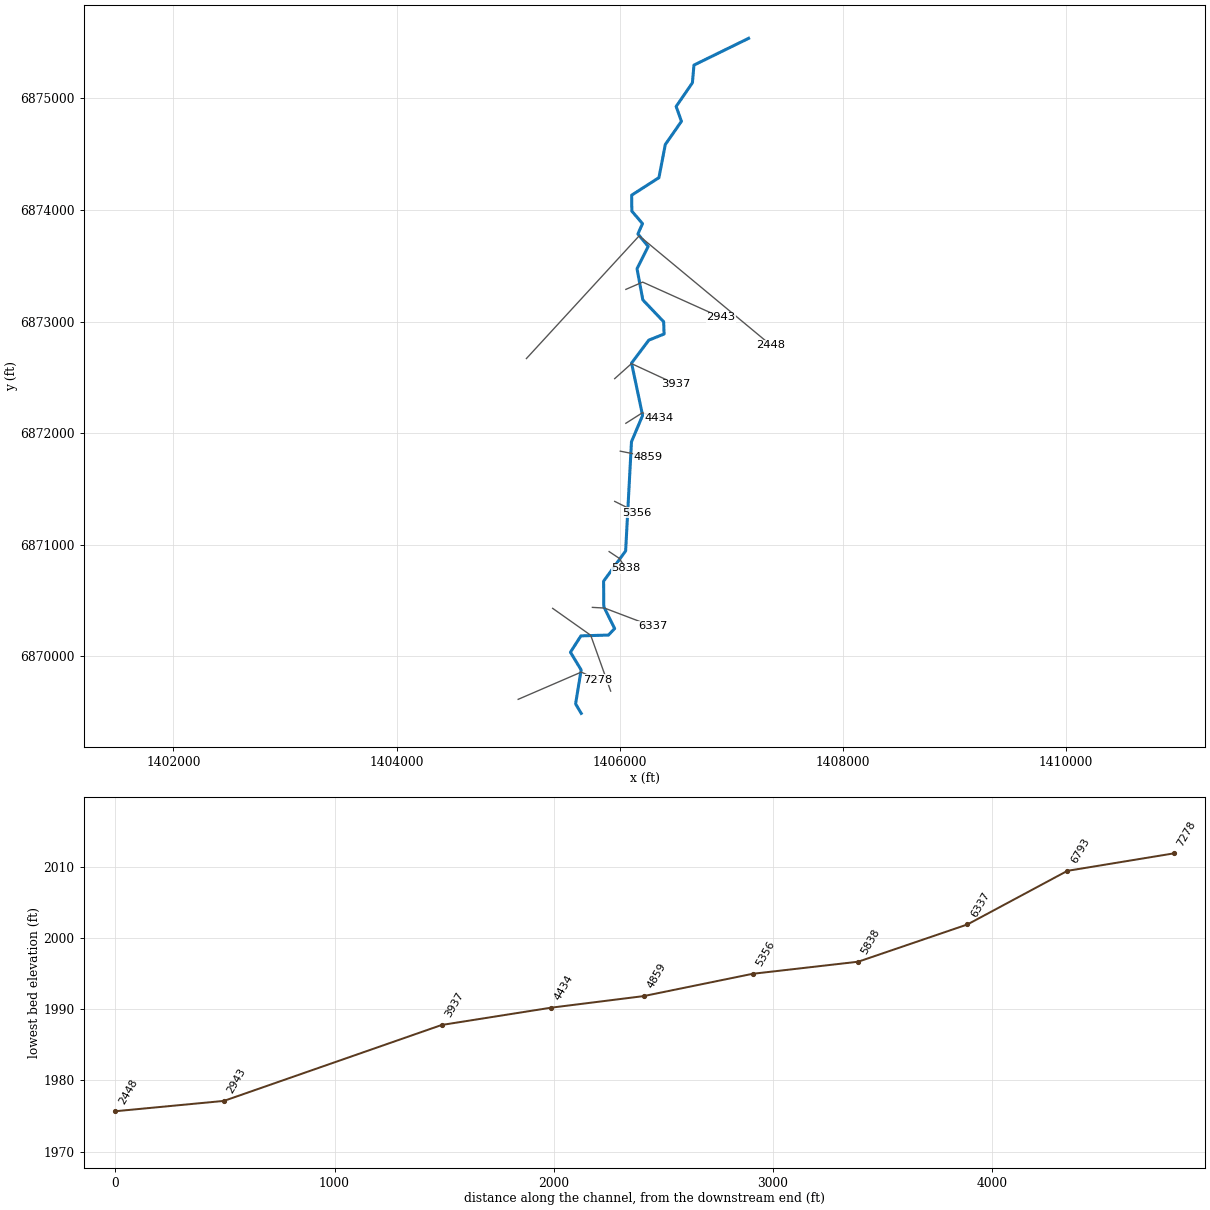
--- Sweetwater Creek Trib 30.prj (project) ---

Proj Title=Sweetwater Creek Trib 30 Base Level Engineering
Current Plan=p01
Default Exp/Contr=0.3,0.1
English Units
Geom File=g01
Flow File=f01
Plan File=p01
BEGIN DESCRIPTION:
Sweetwater Creek Trib 30
END DESCRIPTION:

--- Sweetwater Creek Trib 30.p01 (plan) ---

Plan Title=Multiple Run
Short Identifier=Multiple
Geom File=g01
Flow File=f01
Subcritical Flow
K Sum by GR= 0
Std Step Tol= 0.01
Critical Tol= 0.01
Num of Std Step Trials= 20
Max Error Tol= 0.3
Flow Tol Ratio= 0.001
Split Flow NTrial= 30
Split Flow Tol= 0.02
Split Flow Ratio= 0.02
Log Output Level= 0
Friction Slope Method= 1
Unsteady Friction Slope Method= 2
Unsteady Bridges Friction Slope Method= 1
Parabolic Critical Depth
Global Vel Dist=  1 , 1 , 1
Global Log Level= 0
CheckData=True
Encroach Param= -1, 0, 0, 0
BEGIN DESCRIPTION:
Multiple Run
END DESCRIPTION:

--- Sweetwater Creek Trib 30.f01 (steady flow) ---

Flow Title=Multiple
Number of Profiles=7
Profile Names=10-year,25-year,50-year,1pct_min,100-year,1pct_plu,500-year
River Rch & RM= Sweetwater Creek,Reach-1,7278
     361     518     651     407     813    1621    1281
Boundary for River Rch & Prof#=Sweetwater Creek,Reach-1,1
Up Type=0
Dn Type=3
Dn Slope=0.005
Boundary for River Rch & Prof#=Sweetwater Creek,Reach-1,2
Up Type=0
Dn Type=3
Dn Slope=0.005
Boundary for River Rch & Prof#=Sweetwater Creek,Reach-1,3
Up Type=0
Dn Type=3
Dn Slope=0.005
Boundary for River Rch & Prof#=Sweetwater Creek,Reach-1,4
Up Type=0
Dn Type=3
Dn Slope=0.005
Boundary for River Rch & Prof#=Sweetwater Creek,Reach-1,5
Up Type=0
Dn Type=3
Dn Slope=0.005
Boundary for River Rch & Prof#=Sweetwater Creek,Reach-1,6
Up Type=0
Dn Type=3
Dn Slope=0.005
Boundary for River Rch & Prof#=Sweetwater Creek,Reach-1,7
Up Type=0
Dn Type=3
Dn Slope=0.005

--- Sweetwater Creek Trib 30.g01 (geometry) ---

Geom Title=Existing Conditions

River Reach=Sweetwater Creek,Reach-1
Reach XY= 30
      1405655.00      6869488.00      1405604.59      6869572.83
      1405654.06      6869877.52      1405558.31      6870036.27
      1405652.30      6870182.64      1405899.38      6870189.98
      1405954.48      6870248.45      1405857.24      6870443.93
      1405855.51      6870672.79      1406052.94      6870943.85
      1406105.39      6871922.84      1406205.11      6872158.16
      1406106.04      6872627.56      1406260.48      6872832.74
      1406397.56      6872887.76      1406393.77      6872998.00
      1406207.06      6873193.85      1406155.08      6873472.61
      1406255.04      6873672.66      1406162.84      6873784.60
      1406204.35      6873877.36      1406108.54      6873989.47
      1406106.97      6874132.33      1406351.48      6874289.28
      1406408.55      6874586.53      1406553.20      6874794.11
      1406505.75      6874927.31      1406651.45      6875139.47
      1406665.33      6875298.17      1407155.00      6875538.00

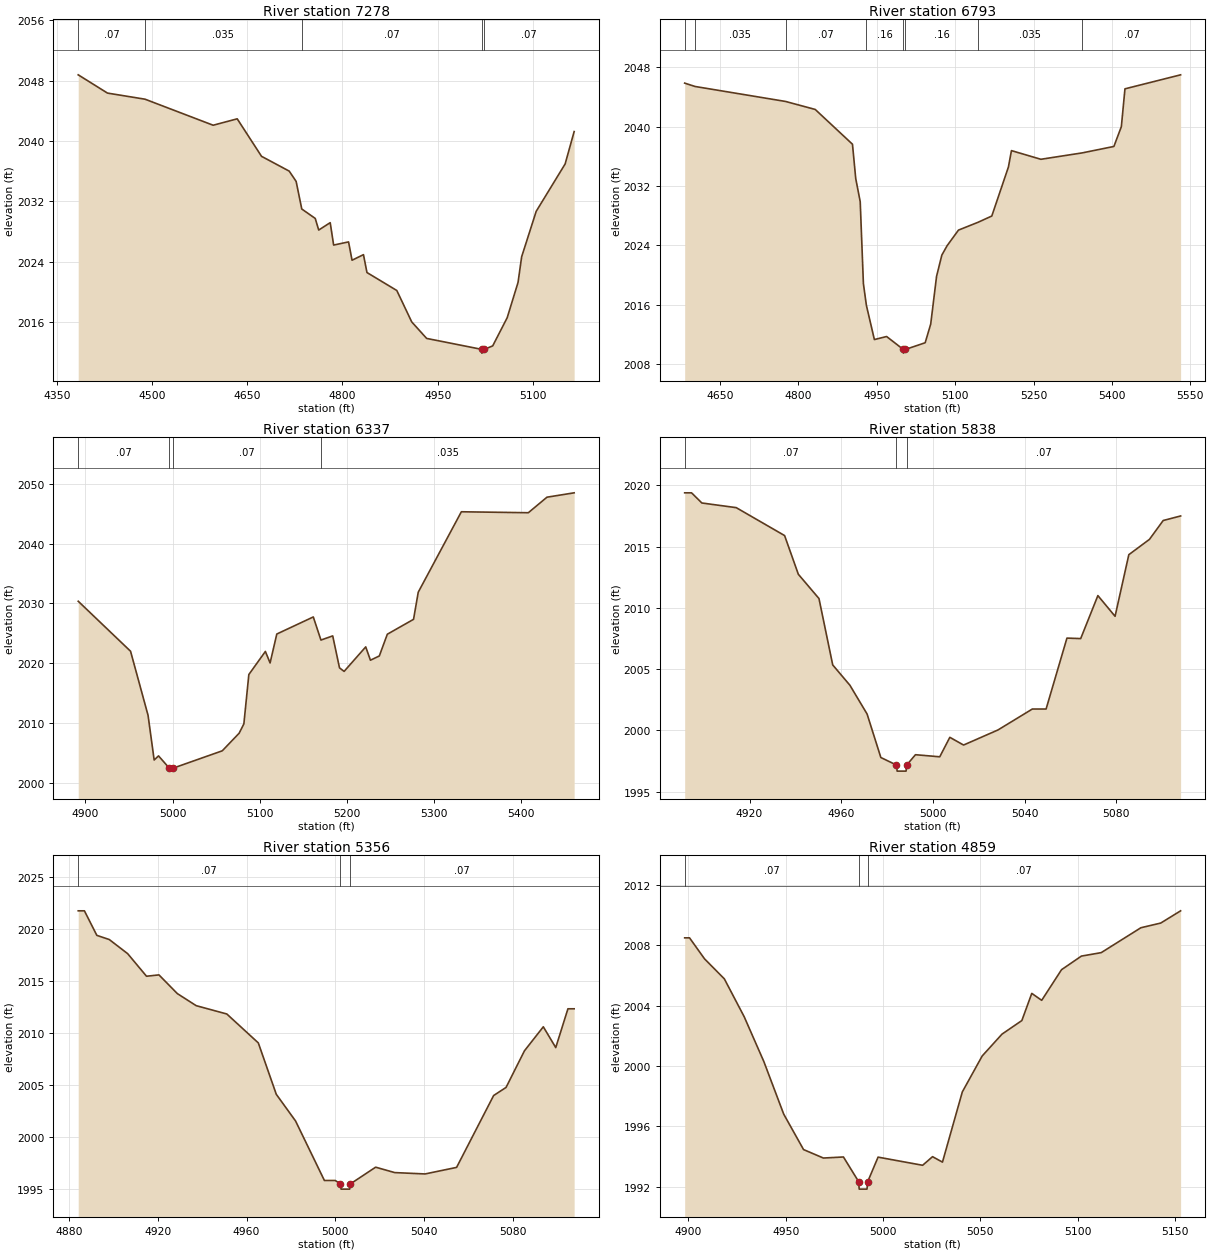
Type RM Length L Ch R = 1,7278,485,485,485
BEGIN DESCRIPTION:
Sweetwater Creek Trib 30 12.0
END DESCRIPTION:
XS GIS Cut Line= 3
      1405089.83      6869613.84      1405655.67      6869858.08
      1405805.04      6869787.98
#Sta/Elev= 30
  4383.7 2048.78  4429.8 2046.36  4489.0 2045.55  4596.3 2042.10  4634.2 2042.95
  4672.5 2037.98  4716.1 2036.02  4727.0 2034.66  4735.9 2031.00  4757.1 2029.75
  4762.6 2028.21  4780.7 2029.19  4786.1 2026.22  4809.6 2026.64  4815.1 2024.21
  4833.1 2024.95  4838.6 2022.58  4885.6 2020.20  4909.1 2016.04  4932.6 2013.85
  5019.3 2012.40  5019.6 2011.90  5023.5 2012.40  5036.7 2012.86  5059.5 2016.59
  5076.6 2021.27  5082.3 2024.67  5105.2 2030.69  5150.8 2036.97  5165.0 2041.26
#Mann=5,-1,0
  4383.7    0.07       0  4489.0   0.035       0  4735.9    0.07       0
  5019.3    0.07       0  5023.5    0.07       0
Bank Sta=5019.3,5023.5
Exp/Cntr=0.3,0.1

Type RM Length L Ch R = 1,6793,456,456,456
BEGIN DESCRIPTION:
Sweetwater Creek Trib 30 11.0
END DESCRIPTION:
XS GIS Cut Line= 3
      1405398.94      6870429.21      1405739.94      6870188.14
      1405918.72      6869687.72
#Sta/Elev= 30
  4582.4 2045.86  4602.2 2045.41  4775.4 2043.39  4832.2 2042.31  4903.5 2037.62
  4909.7 2033.00  4918.3 2029.87  4924.4 2018.82  4930.1 2015.90  4945.4 2011.28
  4968.8 2011.69  5000.7 2009.95  5001.0 2009.45  5004.9 2009.95  5042.6 2010.85
  5053.2 2013.37  5064.4 2019.81  5074.5 2022.67  5084.6 2023.94  5106.3 2026.04
  5144.0 2027.10  5170.1 2027.94  5201.9 2034.55  5207.7 2036.76  5264.0 2035.59
  5342.9 2036.45  5403.7 2037.32  5418.0 2039.99  5424.9 2045.09  5531.4 2046.98
#Mann=8,-1,0
  4582.4    0.07       0  4602.2   0.035       0  4775.4    0.07       0
  4930.1    0.16       0  5000.7    0.07       0  5004.9    0.16       0
  5144.0   0.035       0  5342.9    0.07       0
Bank Sta=5000.7,5004.9
Exp/Cntr=0.3,0.1

Type RM Length L Ch R = 1,6337,499,499,499
BEGIN DESCRIPTION:
Sweetwater Creek Trib 30 10.0
END DESCRIPTION:
XS GIS Cut Line= 3
      1405754.97      6870438.00      1405863.10      6870431.92
      1406294.15      6870268.21
#Sta/Elev= 30
  4891.7 2030.35  4951.8 2021.98  4971.9 2011.25  4978.9 2003.78  4983.9 2004.47
  4996.3 2002.42  4996.6 2001.92  5000.7 2002.42  5057.1 2005.32  5076.5 2008.27
  5081.9 2009.83  5087.6 2018.08  5106.6 2021.95  5112.0 2020.02  5119.7 2024.86
  5161.6 2027.72  5170.4 2023.85  5183.9 2024.55  5191.7 2019.20  5197.0 2018.61
  5221.8 2022.71  5227.2 2020.48  5237.4 2021.19  5246.6 2024.83  5276.7 2027.32
  5282.1 2031.86  5331.6 2045.32  5408.5 2045.16  5429.9 2047.76  5461.1 2048.49
#Mann=4,-1,0
  4891.7    0.07       0  4996.3    0.07       0  5000.7    0.07       0
  5170.4   0.035       0
Bank Sta=4996.3,5000.7
Exp/Cntr=0.3,0.1

Type RM Length L Ch R = 1,5838,482,482,482
BEGIN DESCRIPTION:
Sweetwater Creek Trib 30 9.0
END DESCRIPTION:
XS GIS Cut Line= 3
      1405905.00      6870938.00      1405995.12      6870877.95
      1406055.03      6870787.96
#Sta/Elev= 30
  4891.7 2019.40  4894.7 2019.40  4899.2 2018.57  4914.2 2018.19  4935.3 2015.91
  4941.3 2012.75  4950.3 2010.77  4956.3 2005.35  4963.8 2003.69  4971.3 2001.34
  4977.3 1997.79  4984.1 1997.18  4984.4 1996.68  4988.3 1996.68  4988.6 1997.18
  4992.4 1998.02  5003.0 1997.85  5007.4 1999.44  5013.4 1998.81  5028.4 2000.04
  5043.4 2001.75  5049.4 2001.75  5058.5 2007.54  5064.5 2007.50  5072.0 2011.01
  5079.5 2009.32  5085.5 2014.35  5094.5 2015.60  5100.5 2017.14  5108.1 2017.51
#Mann=3,-1,0
  4891.7    0.07       0  4984.1    0.07       0  4988.6    0.07       0
Bank Sta=4984.1,4988.6
Exp/Cntr=0.3,0.1

Type RM Length L Ch R = 1,5356,497,497,497
BEGIN DESCRIPTION:
Sweetwater Creek Trib 30 8.0
END DESCRIPTION:
XS GIS Cut Line= 3
      1405954.99      6871388.01      1406058.78      6871336.43
      1406154.98      6871288.01
#Sta/Elev= 30
  4884.1 2021.74  4886.9 2021.74  4892.5 2019.38  4898.1 2018.98  4906.4 2017.62
  4914.9 2015.45  4920.5 2015.58  4928.8 2013.78  4937.3 2012.62  4951.1 2011.82
  4965.3 2009.04  4973.4 2004.10  4982.1 2001.53  4995.1 1995.81  5000.0 1995.81
  5002.3 1995.48  5002.6 1994.98  5006.5 1994.98  5006.8 1995.48  5018.2 1997.09
  5026.8 1996.57  5040.5 1996.44  5054.7 1997.07  5071.4 2003.98  5077.0 2004.76
  5085.3 2008.28  5093.8 2010.59  5099.4 2008.59  5104.9 2012.32  5107.7 2012.32
#Mann=3,-1,0
  4884.1    0.07       0  5002.3    0.07       0  5006.8    0.07       0
Bank Sta=5002.3,5006.8
Exp/Cntr=0.3,0.1

Type RM Length L Ch R = 1,4859,425,425,425
BEGIN DESCRIPTION:
Sweetwater Creek Trib 30 7.0
END DESCRIPTION:
XS GIS Cut Line= 3
      1406005.04      6871837.99      1406104.97      6871818.01
      1406254.99      6871788.00
#Sta/Elev= 30
  4898.1 2008.50  4900.6 2008.50  4908.3 2007.11  4918.5 2005.78  4928.7 2003.27
  4938.8 2000.30  4949.0 1996.82  4959.2 1994.47  4969.4 1993.91  4979.7 1993.98
  4987.5 1992.35  4987.8 1991.85  4991.8 1991.85  4992.2 1992.35  4997.5 1993.97
  5020.4 1993.43  5025.5 1994.00  5030.6 1993.64  5040.8 1998.29  5051.0 2000.67
  5061.2 2002.12  5071.4 2003.02  5076.5 2004.82  5081.6 2004.36  5091.8 2006.39
  5102.0 2007.29  5112.2 2007.52  5132.6 2009.17  5142.8 2009.48  5153.0 2010.29
#Mann=3,-1,0
  4898.1    0.07       0  4987.5    0.07       0  4992.2    0.07       0
Bank Sta=4987.5,4992.2
Exp/Cntr=0.3,0.1

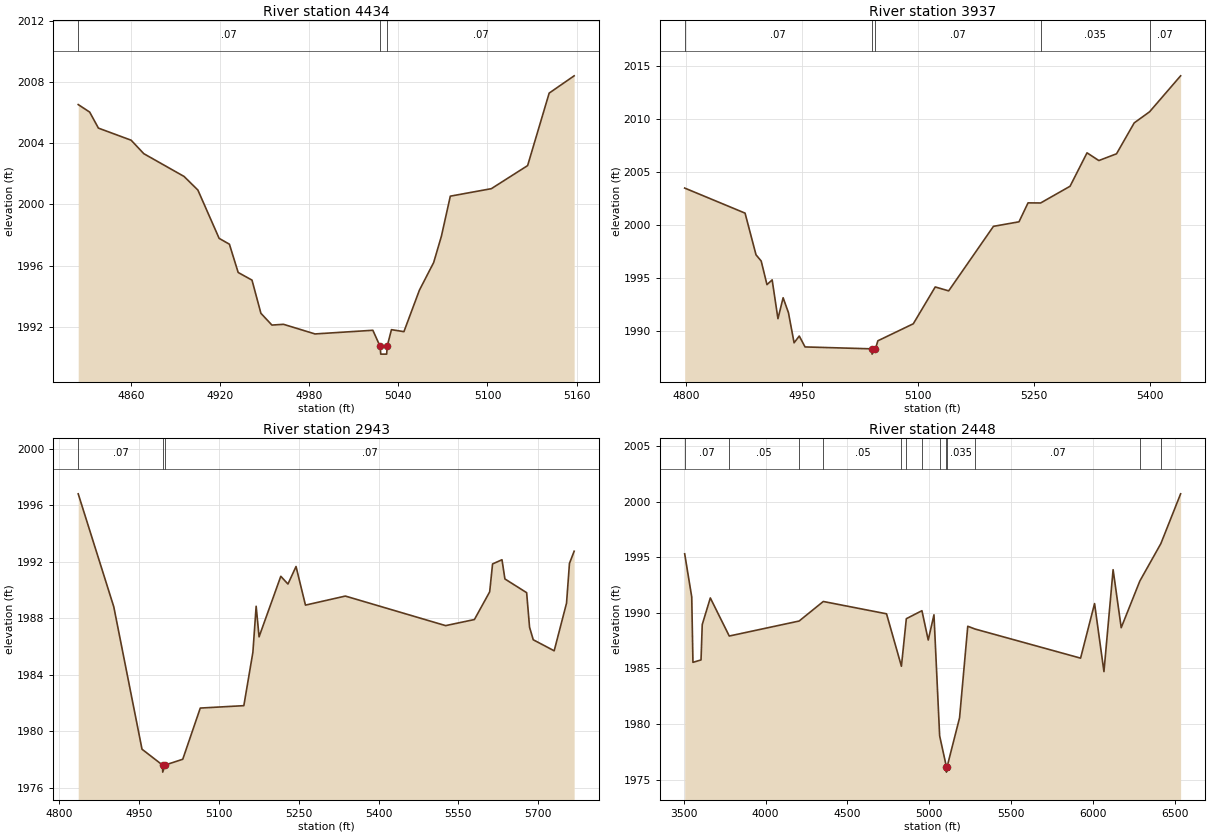
Type RM Length L Ch R = 1,4434,497,497,497
BEGIN DESCRIPTION:
Sweetwater Creek Trib 30 6.0
END DESCRIPTION:
XS GIS Cut Line= 3
      1406054.97      6872087.98      1406202.95      6872181.95
      1406355.03      6872137.99
#Sta/Elev= 30
  4824.7 2006.53  4832.4 2006.04  4838.3 2004.99  4860.3 2004.20  4868.8 2003.32
  4895.9 2001.83  4905.2 2000.94  4919.5 1997.78  4926.4 1997.40  4932.3 1995.55
  4941.6 1995.05  4947.6 1992.88  4955.0 1992.11  4962.8 1992.16  4984.0 1991.53
  5022.9 1991.77  5027.8 1990.71  5028.2 1990.21  5032.2 1990.21  5032.5 1990.71
  5035.4 1991.81  5043.8 1991.68  5054.2 1994.39  5063.8 1996.20  5069.0 1997.92
  5075.0 2000.54  5102.6 2001.03  5127.0 2002.54  5141.5 2007.28  5158.3 2008.41
#Mann=3,-1,0
  4824.7    0.07       0  5027.8    0.07       0  5032.5    0.07       0
Bank Sta=5027.8,5032.5
Exp/Cntr=0.3,0.1

Type RM Length L Ch R = 1,3937,994,994,994
BEGIN DESCRIPTION:
Sweetwater Creek Trib 30 5.0
END DESCRIPTION:
XS GIS Cut Line= 3
      1405954.97      6872487.98      1406105.37      6872622.84
      1406504.99      6872438.00
#Sta/Elev= 30
  4798.0 2003.49  4876.2 2001.12  4890.4 1997.18  4897.1 1996.59  4904.6 1994.36
  4911.3 1994.81  4918.8 1991.14  4925.5 1993.12  4932.4 1991.71  4939.7 1988.86
  4946.4 1989.50  4953.9 1988.47  5040.4 1988.29  5040.7 1987.79  5045.1 1988.29
  5048.2 1989.05  5094.1 1990.66  5122.5 1994.14  5139.9 1993.77  5197.9 1999.87
  5231.0 2000.30  5242.7 2002.09  5259.0 2002.08  5297.1 2003.66  5319.1 2006.82
  5334.4 2006.09  5357.3 2006.73  5380.2 2009.65  5400.1 2010.70  5440.3 2014.10
#Mann=5,-1,0
  4798.0    0.07       0  5040.4    0.07       0  5045.1    0.07       0
  5259.0   0.035       0  5400.1    0.07       0
Bank Sta=5040.4,5045.1
Exp/Cntr=0.3,0.1

Type RM Length L Ch R = 1,2943,495,495,495
BEGIN DESCRIPTION:
Sweetwater Creek Trib 30 4.0
END DESCRIPTION:
XS GIS Cut Line= 3
      1406055.03      6873288.01      1406205.42      6873353.18
      1406905.00      6873038.00
#Sta/Elev= 30
  4836.1 1996.80  4902.9 1988.81  4955.9 1978.74  4994.4 1977.62  4994.8 1977.12
  4999.2 1977.62  5032.4 1978.03  5065.3 1981.65  5147.1 1981.82  5164.1 1985.60
  5170.2 1988.85  5175.7 1986.69  5216.5 1990.97  5229.9 1990.42  5245.1 1991.66
  5262.8 1988.93  5337.7 1989.57  5526.0 1987.48  5580.0 1987.91  5608.7 1989.87
  5614.1 1991.84  5631.8 1992.14  5637.3 1990.78  5678.1 1989.81  5683.6 1987.36
  5690.5 1986.48  5729.8 1985.70  5753.0 1989.07  5758.5 1991.88  5767.3 1992.74
#Mann=3,-1,0
  4836.1    0.07       0  4994.4    0.07       0  4999.2    0.07       0
Bank Sta=4994.4,4999.2
Exp/Cntr=0.3,0.1

Type RM Length L Ch R = 1,2448,0,0,0
BEGIN DESCRIPTION:
Sweetwater Creek Trib 30 292
END DESCRIPTION:
XS GIS Cut Line= 3
      1405163.72      6872668.09      1406174.35      6873767.99
      1407355.02      6872787.99
#Sta/Elev= 30
  3506.3 1995.32  3549.4 1991.44  3556.8 1985.55  3606.1 1985.77  3613.5 1988.95
  3662.9 1991.35  3778.5 1987.92  4205.1 1989.27  4352.7 1991.03  4738.8 1989.92
  4829.7 1985.20  4859.6 1989.48  4954.9 1990.20  4993.4 1987.56  5028.4 1989.83
  5063.1 1978.93  5104.1 1976.17  5104.5 1975.67  5108.9 1976.17  5184.7 1980.56
  5234.8 1988.80  5279.3 1988.55  5923.6 1985.93  6009.0 1990.84  6066.3 1984.72
  6122.2 1993.89  6171.7 1988.67  6285.4 1992.87  6413.8 1996.24  6534.4 2000.72
#Mann=13,-1,0
  3506.3    0.07       0  3778.5    0.05       0  4205.1    0.07       0
  4352.7    0.05       0  4829.7    0.07       0  4859.6    0.05       0
  4954.9    0.07       0  5063.1   0.035       0  5104.1    0.07       0
  5108.9   0.035       0  5279.3    0.07       0  6285.4   0.035       0
  6413.8    0.07       0
Bank Sta=5104.1,5108.9
Exp/Cntr=0.3,0.1

Chan Stop Cuts=-1