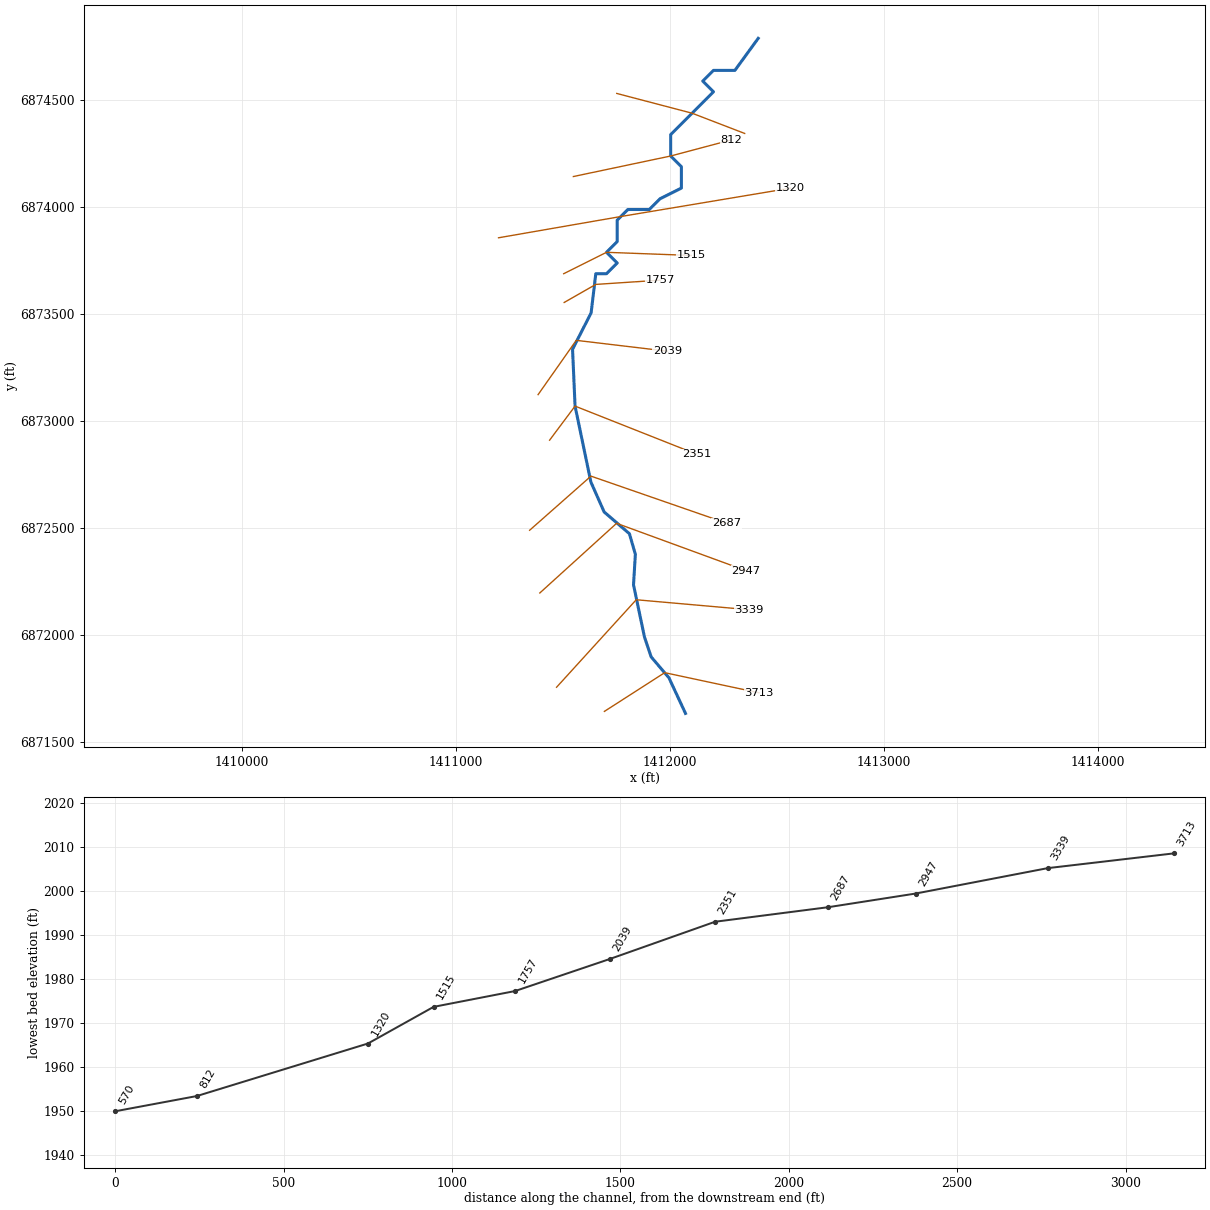
--- Sweetwater Creek Trib 30_5.prj (project) ---

Proj Title=Sweetwater Creek Trib 30_5 Base Level Engineering
Current Plan=p01
Default Exp/Contr=0.3,0.1
English Units
Geom File=g01
Flow File=f01
Plan File=p01
Y Axis Title=Elevation
X Axis Title(PF)=Main Channel Distance
X Axis Title(XS)=Station
BEGIN DESCRIPTION:
Sweetwater Creek Trib 30_5
END DESCRIPTION:
DSS Export Rating Curves= 0
DSS Export Rating Curve Sorted= 0
DSS Export Volume Flow Curves= 0
DXF OffsetX= 0
DXF OffsetY= 0
DXF ScaleX= 1
DXF ScaleY= 10

--- Sweetwater Creek Trib 30_5.p01 (plan) ---

Plan Title=Multiple Run
Short Identifier=Multiple
Geom File=g01
Flow File=f01
Subcritical Flow
K Sum by GR= 0
Std Step Tol= 0.01
Critical Tol= 0.01
Num of Std Step Trials= 20
Max Error Tol= 0.3
Flow Tol Ratio= 0.001
Split Flow NTrial= 30
Split Flow Tol= 0.02
Split Flow Ratio= 0.02
Log Output Level= 0
Friction Slope Method= 1
Unsteady Friction Slope Method= 2
Unsteady Bridges Friction Slope Method= 1
Parabolic Critical Depth
Global Vel Dist=  1 , 1 , 1
Global Log Level= 0
CheckData=True
Encroach Param= -1, 0, 0, 0
BEGIN DESCRIPTION:
Multiple Run
END DESCRIPTION:

--- Sweetwater Creek Trib 30_5.f01 (steady flow) ---

Flow Title=Multiple
Program Version=4.10
Number of Profiles= 7
Profile Names=10-year,25-year,50-year,1pct_min,100-year,1pct_plu,500-year
River Rch & RM=Sweetwater Creek,Reach-1         ,3713
     223     316     395     246     491     980     768
River Rch & RM=Sweetwater Creek,Reach-1         ,2351
     223     316     395     246     491     980     768
Boundary for River Rch & Prof#=Sweetwater Creek,Reach-1         , 1
Up Type= 0
Dn Type= 3
Dn Slope=0.005
Boundary for River Rch & Prof#=Sweetwater Creek,Reach-1         , 2
Up Type= 0
Dn Type= 3
Dn Slope=0.005
Boundary for River Rch & Prof#=Sweetwater Creek,Reach-1         , 3
Up Type= 0
Dn Type= 3
Dn Slope=0.005
Boundary for River Rch & Prof#=Sweetwater Creek,Reach-1         , 4
Up Type= 0
Dn Type= 3
Dn Slope=0.005
Boundary for River Rch & Prof#=Sweetwater Creek,Reach-1         , 5
Up Type= 0
Dn Type= 3
Dn Slope=0.005
Boundary for River Rch & Prof#=Sweetwater Creek,Reach-1         , 6
Up Type= 0
Dn Type= 3
Dn Slope=0.005
Boundary for River Rch & Prof#=Sweetwater Creek,Reach-1         , 7
Up Type= 0
Dn Type= 3
Dn Slope=0.005
DSS Import GetInterval= 0
DSS Import GetPeak= 0
DSS Import FillOption= 0

--- Sweetwater Creek Trib 30_5.g01 (geometry) ---

Geom Title=Existing Conditions

River Reach=Sweetwater Creek,Reach-1
Reach XY= 30
      1412074.15      6871633.56      1411997.06      6871799.43
      1411913.73      6871897.52      1411882.48      6871990.41
      1411831.27      6872234.33      1411839.95      6872376.69
      1411812.17      6872473.04      1411694.11      6872574.61
      1411631.92      6872714.92      1411558.09      6873069.32
      1411546.37      6873334.95      1411633.18      6873505.08
      1411655.00      6873688.00      1411705.00      6873688.00
      1411755.00      6873738.00      1411705.00      6873788.00
      1411755.00      6873838.00      1411755.00      6873938.00
      1411805.00      6873988.00      1411905.00      6873988.00
      1411955.00      6874038.00      1412055.00      6874088.00
      1412055.00      6874188.00      1412005.00      6874238.00
      1412005.00      6874338.00      1412205.00      6874538.00
      1412155.00      6874588.00      1412205.00      6874638.00
      1412305.00      6874638.00      1412414.10      6874787.83

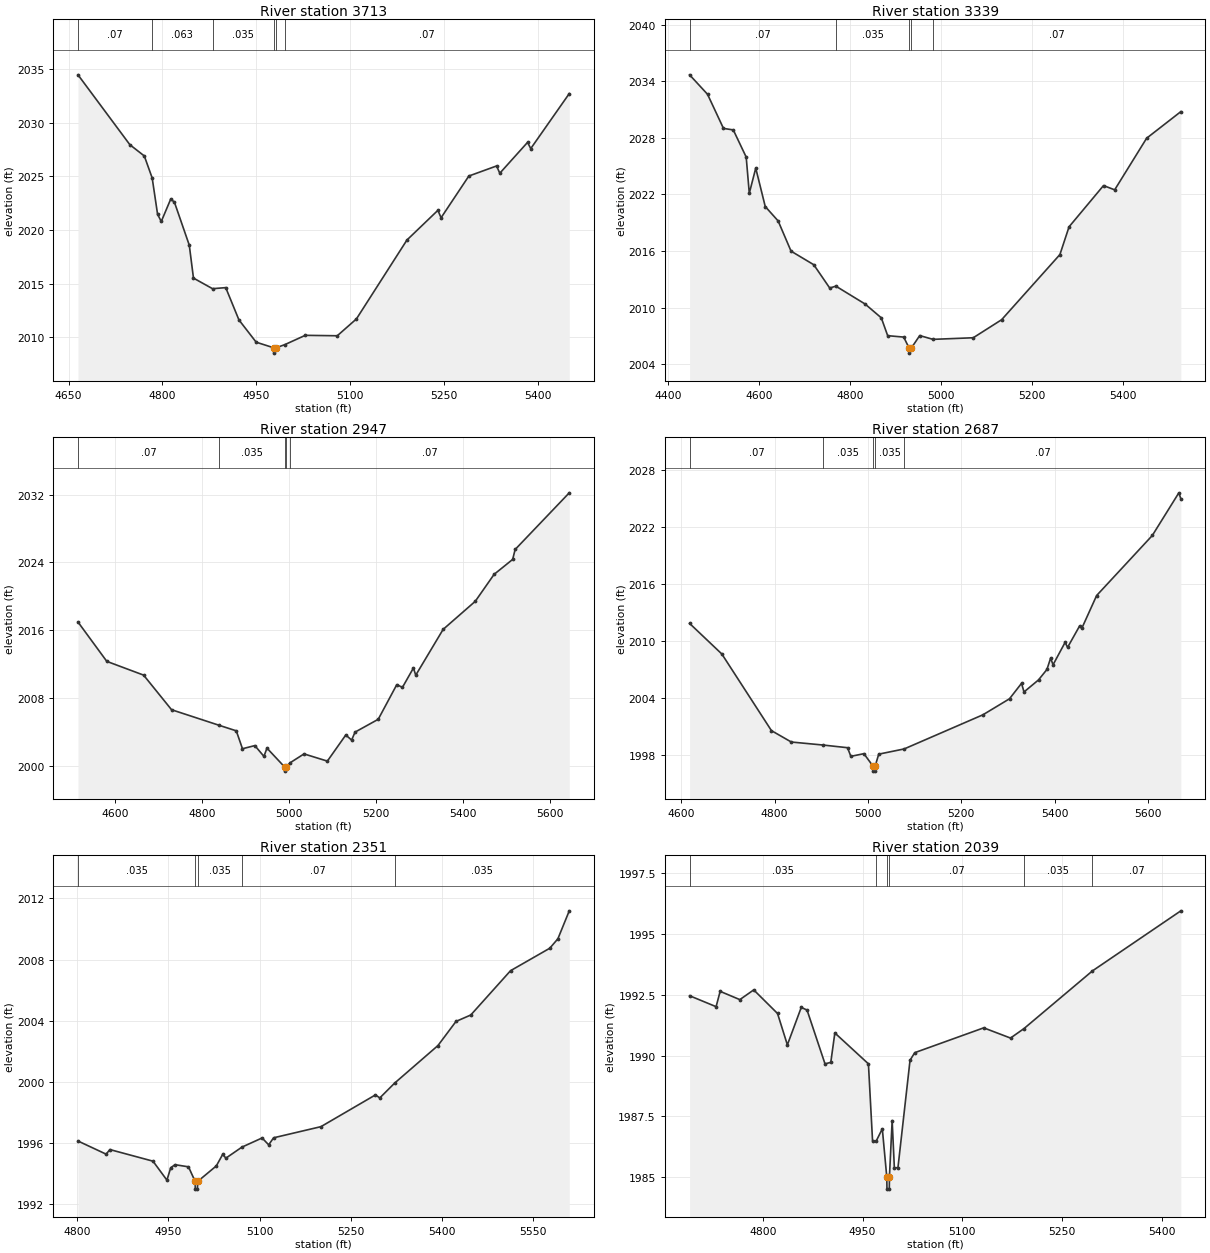
Type RM Length L Ch R = 1,3713,374,374,374
BEGIN DESCRIPTION:
Sweetwater Creek Trib 30_5 4184
END DESCRIPTION:
XS GIS Cut Line= 3
      1411695.15      6871642.82      1411977.10      6871823.74
      1412417.87      6871729.63
#Sta/Elev= 30
  4665.0 2034.48  4748.0 2027.96  4771.1 2026.91  4783.7 2024.85  4792.3 2021.47
  4798.2 2020.80  4813.4 2022.90  4819.3 2022.59  4843.0 2018.59  4849.7 2015.52
  4880.2 2014.53  4901.3 2014.63  4922.4 2011.62  4950.0 2009.54  4977.9 2009.02
  4978.1 2008.52  4981.9 2009.02  4995.7 2009.31  5028.5 2010.18  5079.7 2010.14
  5110.3 2011.71  5191.1 2019.07  5240.6 2021.84  5245.7 2021.15  5290.1 2025.04
  5334.5 2025.98  5339.6 2025.30  5384.0 2028.18  5389.1 2027.60  5450.7 2032.73
#Mann=6,-1,0
  4665.0    0.07       0  4783.7   0.063       0  4880.2   0.035       0
  4977.9    0.07       0  4981.9   0.035       0  4995.7    0.07       0
Bank Sta=4977.9,4981.9
Exp/Cntr=0.3,0.1

Type RM Length L Ch R = 1,3339,392,392,392
BEGIN DESCRIPTION:
Sweetwater Creek Trib 30_5 4183
END DESCRIPTION:
XS GIS Cut Line= 3
      1411471.67      6871755.71      1411843.97      6872164.48
      1412370.02      6872118.10
#Sta/Elev= 30
  4447.1 2034.67  4486.6 2032.61  4521.7 2028.99  4543.3 2028.83  4571.7 2025.95
  4578.5 2022.11  4592.7 2024.78  4613.6 2020.71  4642.0 2019.18  4670.4 2015.98
  4720.4 2014.54  4755.5 2012.07  4769.0 2012.27  4833.2 2010.38  4869.0 2008.91
  4883.0 2007.02  4918.3 2006.87  4930.5 2005.67  4930.8 2005.17  4934.5 2005.67
  4953.5 2007.03  4982.8 2006.63  5071.3 2006.80  5133.7 2008.71  5262.0 2015.62
  5282.1 2018.56  5357.9 2022.93  5382.5 2022.48  5452.8 2027.95  5528.1 2030.77
#Mann=5,-1,0
  4447.1    0.07       0  4769.0   0.035       0  4930.5    0.07       0
  4934.5   0.035       0  4982.8    0.07       0
Bank Sta=4930.5,4934.5
Exp/Cntr=0.3,0.1

Type RM Length L Ch R = 1,2947,260,260,260
BEGIN DESCRIPTION:
Sweetwater Creek Trib 30_5 4182
END DESCRIPTION:
XS GIS Cut Line= 3
      1411393.50      6872196.20      1411752.27      6872521.66
      1412357.07      6872300.39
#Sta/Elev= 30
  4515.6 2016.97  4581.8 2012.33  4666.3 2010.71  4730.5 2006.63  4840.6 2004.78
  4879.2 2004.14  4893.4 2002.03  4921.8 2002.40  4942.7 2001.13  4949.7 2002.10
  4990.0 1999.89  4990.3 1999.39  4994.0 1999.89  5003.0 2000.38  5034.8 2001.42
  5088.4 2000.57  5130.7 2003.65  5144.1 2003.05  5152.0 2003.99  5205.2 2005.50
  5247.8 2009.58  5260.9 2009.27  5286.1 2011.55  5291.4 2010.70  5354.3 2016.10
  5428.1 2019.41  5471.4 2022.59  5514.0 2024.35  5519.7 2025.52  5644.0 2032.20
#Mann=5,-1,0
  4515.6    0.07       0  4840.6   0.035       0  4990.0   0.035       0
  4994.0   0.035       0  5003.0    0.07       0
Bank Sta=4990,4994
Exp/Cntr=0.3,0.1

Type RM Length L Ch R = 1,2687,336,336,336
BEGIN DESCRIPTION:
Sweetwater Creek Trib 30_5 4181
END DESCRIPTION:
XS GIS Cut Line= 3
      1411345.81      6872489.22      1411632.48      6872742.14
      1412266.26      6872522.38
#Sta/Elev= 30
  4617.7 2011.86  4686.9 2008.63  4793.2 2000.55  4835.8 1999.35  4904.1 1999.03
  4956.3 1998.75  4963.4 1997.84  4991.4 1998.12  5011.3 1996.78  5011.5 1996.28
  5015.0 1996.28  5015.3 1996.78  5023.2 1998.07  5077.7 1998.62  5246.5 2002.22
  5303.5 2003.91  5329.3 2005.54  5334.6 2004.63  5365.7 2005.90  5383.7 2007.00
  5391.6 2008.19  5396.9 2007.50  5422.7 2009.86  5428.0 2009.33  5453.9 2011.60
  5459.2 2011.42  5490.3 2014.80  5609.6 2021.13  5666.5 2025.63  5670.8 2025.00
#Mann=5,-1,0
  4617.7    0.07       0  4904.1   0.035       0  5011.3   0.035       0
  5015.3   0.035       0  5077.7    0.07       0
Bank Sta=5011.3,5015.3
Exp/Cntr=0.3,0.1

Type RM Length L Ch R = 1,2351,312,312,312
BEGIN DESCRIPTION:
Sweetwater Creek Trib 30_5 4180
END DESCRIPTION:
XS GIS Cut Line= 3
      1411439.09      6872910.19      1411558.09      6873069.32
      1412124.85      6872845.10
#Sta/Elev= 30
  4801.3 1996.12  4847.6 1995.26  4853.8 1995.56  4924.7 1994.80  4947.6 1993.56
  4953.9 1994.37  4960.9 1994.57  4983.1 1994.43  4994.1 1993.47  4994.3 1992.97
  4997.8 1992.97  4998.1 1993.47  5028.9 1994.49  5039.3 1995.24  5044.7 1995.00
  5071.0 1995.72  5104.2 1996.32  5115.0 1995.87  5123.1 1996.33  5201.0 1997.06
  5290.7 1999.14  5297.8 1998.94  5322.2 1999.91  5393.5 2002.37  5423.2 2003.95
  5447.5 2004.37  5512.9 2007.27  5577.4 2008.74  5590.8 2009.36  5609.5 2011.19
#Mann=5,-1,0
  4801.3   0.035       0  4994.1   0.035       0  4998.1   0.035       0
  5071.0    0.07       0  5322.2   0.035       0
Bank Sta=4994.1,4998.1
Exp/Cntr=0.3,0.1

Type RM Length L Ch R = 1,2039,282,282,282
BEGIN DESCRIPTION:
Sweetwater Creek Trib 30_5 3886
END DESCRIPTION:
XS GIS Cut Line= 3
      1411385.28      6873122.88      1411563.73      6873376.61
      1411989.43      6873326.00
#Sta/Elev= 30
  4689.8 1992.46  4729.7 1992.01  4735.8 1992.64  4765.4 1992.30  4786.3 1992.70
  4822.1 1991.73  4836.9 1990.44  4857.8 1991.98  4866.5 1991.87  4893.5 1989.66
  4902.2 1989.72  4908.3 1990.93  4958.8 1989.66  4965.0 1986.50  4970.2 1986.47
  4979.7 1986.99  4986.4 1985.01  4986.7 1984.51  4990.2 1984.51  4990.4 1985.01
  4994.5 1987.33  4997.8 1985.39  5003.2 1985.39  5021.4 1989.81  5028.5 1990.12
  5132.2 1991.14  5172.5 1990.72  5192.8 1991.11  5295.7 1993.48  5428.7 1995.95
#Mann=6,-1,0
  4689.8   0.035       0  4970.2    0.07       0  4986.4    0.07       0
  4990.4    0.07       0  5192.8   0.035       0  5295.7    0.07       0
Bank Sta=4986.4,4990.4
Exp/Cntr=0.3,0.1

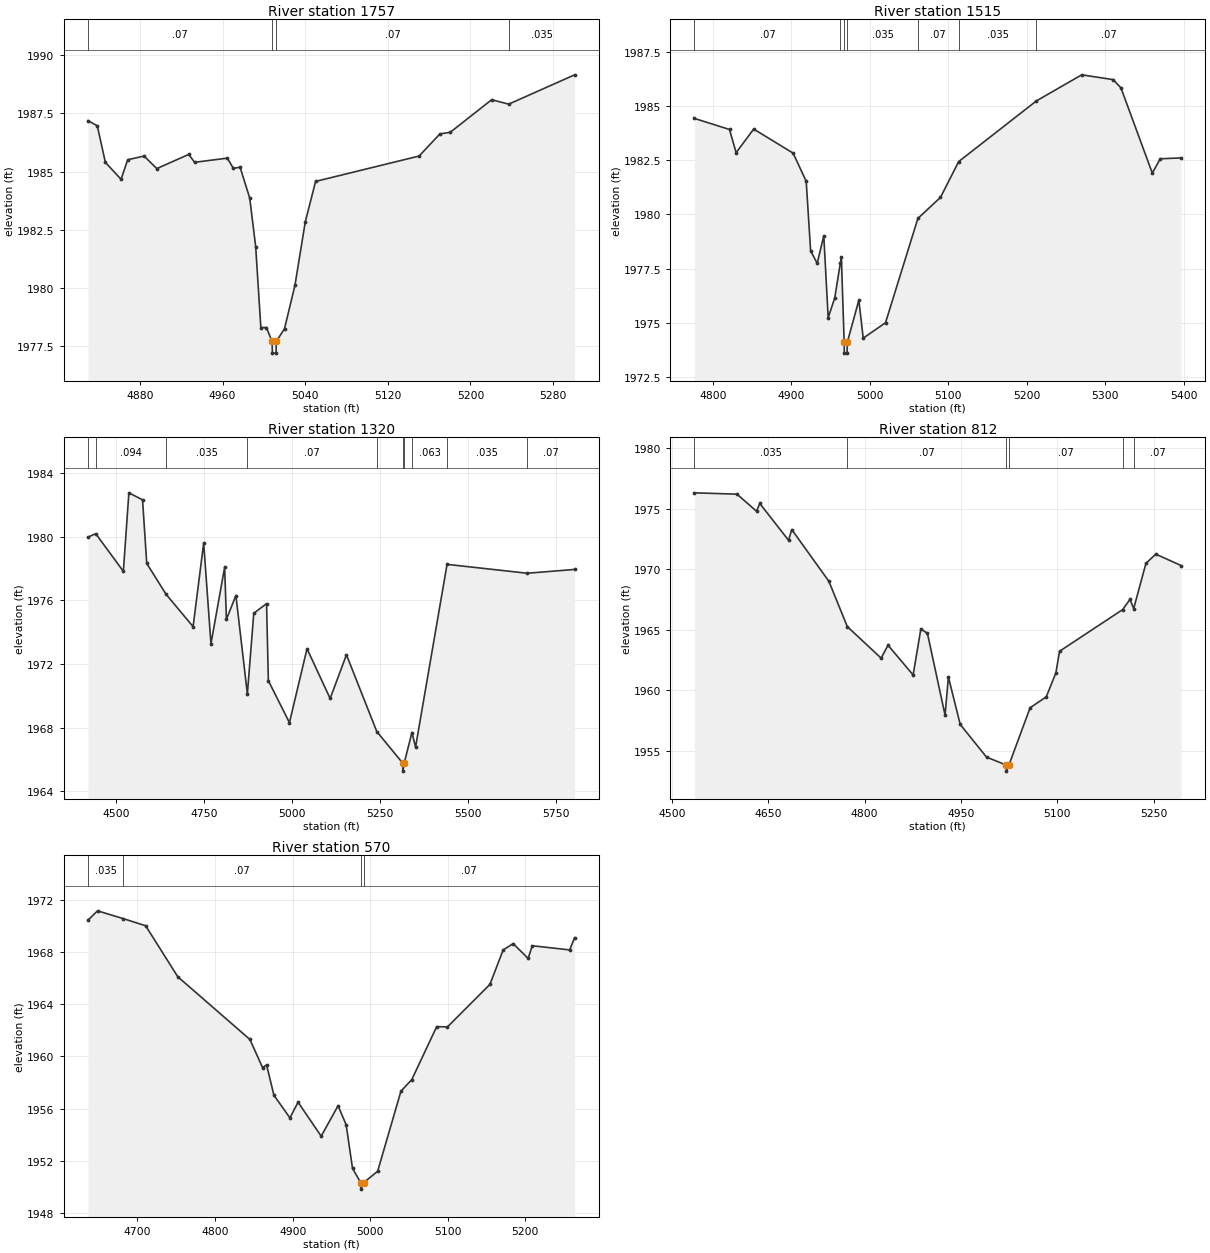
Type RM Length L Ch R = 1,1757,242,242,242
BEGIN DESCRIPTION:
Sweetwater Creek Trib 30_5 3885
END DESCRIPTION:
XS GIS Cut Line= 3
      1411507.20      6873553.60      1411655.00      6873638.00
      1411955.15      6873657.77
#Sta/Elev= 30
  4829.8 1987.19  4838.8 1986.97  4846.6 1985.40  4861.8 1984.67  4868.2 1985.51
  4884.1 1985.67  4896.4 1985.13  4927.3 1985.74  4933.0 1985.40  4964.7 1985.58
  4970.5 1985.14  4977.0 1985.19  4986.3 1983.87  4992.1 1981.78  4997.1 1978.30
  5002.5 1978.30  5008.0 1977.70  5008.3 1977.20  5011.8 1977.20  5012.0 1977.70
  5020.0 1978.25  5030.1 1980.11  5040.1 1982.84  5050.1 1984.58  5150.3 1985.67
  5170.4 1986.62  5180.4 1986.69  5220.5 1988.09  5237.0 1987.90  5300.8 1989.16
#Mann=4,-1,0
  4829.8    0.07       0  5008.0    0.07       0  5012.0    0.07       0
  5237.0   0.035       0
Bank Sta=5008,5012
Exp/Cntr=0.3,0.1

Type RM Length L Ch R = 1,1515,195,195,195
BEGIN DESCRIPTION:
Sweetwater Creek Trib 30.5 3.0
END DESCRIPTION:
XS GIS Cut Line= 3
      1411505.01      6873688.00      1411705.00      6873788.00
      1412101.63      6873773.29
#Sta/Elev= 30
  4776.4 1984.42  4821.1 1983.91  4829.5 1982.84  4851.9 1983.93  4902.2 1982.82
  4918.9 1981.52  4924.5 1978.32  4932.9 1977.74  4941.3 1979.01  4946.9 1975.23
  4955.3 1976.15  4962.5 1977.77  4963.7 1978.04  4967.3 1974.10  4967.5 1973.60
  4971.0 1973.60  4971.3 1974.10  4986.0 1976.04  4991.6 1974.29  5020.0 1975.00
  5061.3 1979.81  5090.1 1980.78  5113.3 1982.43  5212.5 1985.23  5270.2 1986.43
  5310.2 1986.21  5320.2 1985.83  5360.2 1981.90  5370.3 1982.56  5396.9 1982.60
#Mann=7,-1,0
  4776.4    0.07       0  4962.5   0.035       0  4967.3   0.035       0
  4971.3   0.035       0  5061.3    0.07       0  5113.3   0.035       0
  5212.5    0.07       0
Bank Sta=4967.3,4971.3
Exp/Cntr=0.3,0.1

Type RM Length L Ch R = 1,1320,508,508,508
BEGIN DESCRIPTION:
Sweetwater Creek Trib 30.5 2.0
END DESCRIPTION:
XS GIS Cut Line= 3
      1411200.41      6873855.85      1411772.24      6873955.24
      1412565.24      6874087.79
#Sta/Elev= 30
  4419.6 1979.98  4441.6 1980.20  4520.2 1977.83  4535.9 1982.77  4574.8 1982.33
  4586.7 1978.33  4641.6 1976.39  4718.6 1974.35  4748.7 1979.61  4769.4 1973.27
  4808.3 1978.08  4813.4 1974.81  4840.4 1976.31  4873.0 1970.11  4891.2 1975.19
  4927.6 1975.80  4932.7 1970.95  4992.7 1968.31  5042.7 1972.96  5108.5 1969.83
  5154.9 1972.58  5241.2 1967.75  5315.1 1965.76  5315.3 1965.26  5319.1 1965.76
  5341.2 1967.69  5351.5 1966.77  5441.1 1978.27  5669.2 1977.71  5804.0 1977.95
#Mann=10,-1,0
  4419.6    0.07       0  4441.6   0.094       0  4641.6   0.035       0
  4873.0    0.07       0  5241.2   0.035       0  5315.1    0.07       0
  5319.1   0.035       0  5341.2   0.063       0  5441.1   0.035       0
  5669.2    0.07       0
Bank Sta=5315.1,5319.1
Exp/Cntr=0.3,0.1

Type RM Length L Ch R = 1,812,242,242,242
BEGIN DESCRIPTION:
Sweetwater Creek Trib 30.5 1.1
END DESCRIPTION:
XS GIS Cut Line= 3
      1411550.21      6874142.04      1412005.00      6874238.00
      1412287.89      6874313.15
#Sta/Elev= 30
  4535.2 1976.32  4601.4 1976.21  4631.8 1974.80  4636.9 1975.44  4681.6 1972.40
  4686.7 1973.28  4744.5 1969.00  4773.1 1965.26  4825.8 1962.65  4836.5 1963.72
  4875.6 1961.26  4887.6 1965.06  4897.8 1964.71  4925.3 1957.94  4930.5 1961.09
  4948.9 1957.17  4989.8 1954.47  5020.7 1953.81  5020.9 1953.31  5024.7 1953.81
  5057.7 1958.55  5082.8 1959.45  5097.8 1961.43  5103.5 1963.22  5201.6 1966.66
  5213.2 1967.51  5218.9 1966.75  5238.0 1970.49  5253.3 1971.25  5292.7 1970.31
#Mann=6,-1,0
  4535.2   0.035       0  4773.1    0.07       0  5020.7    0.07       0
  5024.7    0.07       0  5201.6   0.035       0  5218.9    0.07       0
Bank Sta=5020.7,5024.7
Exp/Cntr=0.3,0.1

Type RM Length L Ch R = 1,570,0,0,0
BEGIN DESCRIPTION:
Sweetwater Creek Trib 30.5 1.0
END DESCRIPTION:
XS GIS Cut Line= 3
      1411753.10      6874530.30      1412105.00      6874438.00
      1412350.93      6874343.39
#Sta/Elev= 30
  4636.2 1970.43  4648.5 1971.14  4681.8 1970.54  4710.5 1970.00  4751.9 1966.10
  4844.9 1961.30  4861.2 1959.15  4866.4 1959.35  4875.9 1957.03  4896.5 1955.30
  4907.0 1956.50  4936.8 1953.90  4958.6 1956.23  4969.0 1954.77  4977.2 1951.44
  4987.7 1950.35  4987.9 1949.85  4991.7 1950.35  5009.6 1951.22  5039.6 1957.34
  5053.6 1958.23  5085.7 1962.28  5099.6 1962.26  5154.3 1965.51  5171.4 1968.15
  5184.3 1968.63  5203.6 1967.50  5208.9 1968.47  5257.1 1968.15  5263.5 1969.09
#Mann=4,-1,0
  4636.2   0.035       0  4681.8    0.07       0  4987.7    0.07       0
  4991.7    0.07       0
Bank Sta=4987.7,4991.7
Exp/Cntr=0.3,0.1

Chan Stop Cuts=-1