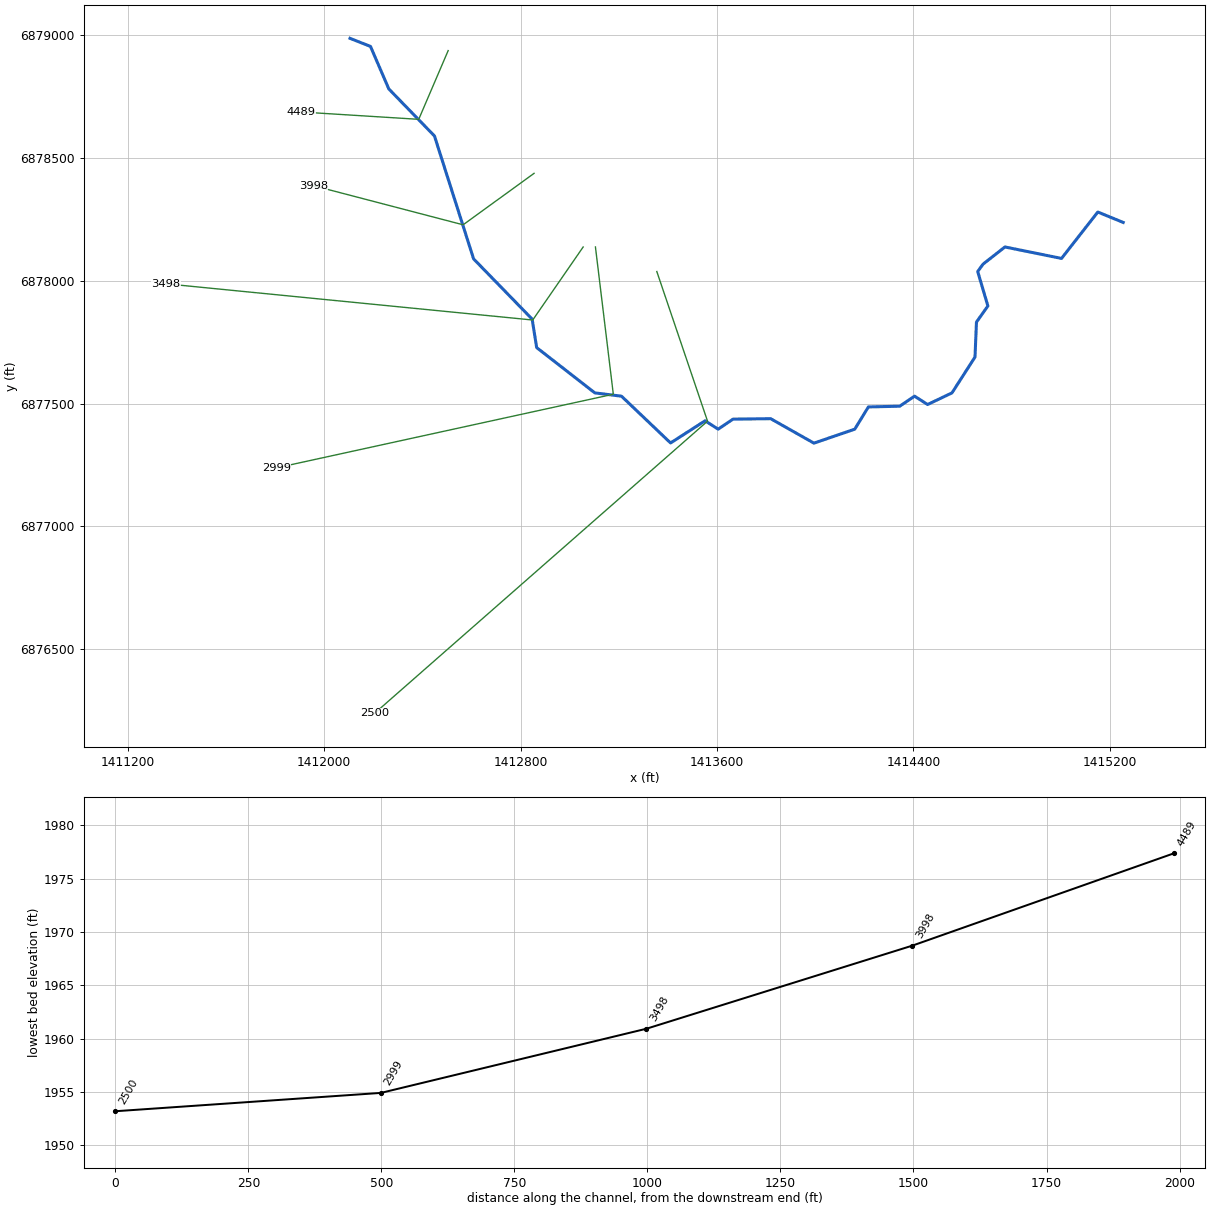
--- Sweetwater Creek Trib 31.prj (project) ---

Proj Title=Sweetwater Creek Trib 31 Base Level Engineering
Current Plan=p01
Default Exp/Contr=0.3,0.1
English Units
Geom File=g01
Flow File=f01
Plan File=p01
BEGIN DESCRIPTION:
Sweetwater Creek Trib 31
END DESCRIPTION:

--- Sweetwater Creek Trib 31.p01 (plan) ---

Plan Title=Multiple Run
Short Identifier=Multiple
Geom File=g01
Flow File=f01
Subcritical Flow
K Sum by GR= 0
Std Step Tol= 0.01
Critical Tol= 0.01
Num of Std Step Trials= 20
Max Error Tol= 0.3
Flow Tol Ratio= 0.001
Split Flow NTrial= 30
Split Flow Tol= 0.02
Split Flow Ratio= 0.02
Log Output Level= 0
Friction Slope Method= 1
Unsteady Friction Slope Method= 2
Unsteady Bridges Friction Slope Method= 1
Parabolic Critical Depth
Global Vel Dist=  1 , 1 , 1
Global Log Level= 0
CheckData=True
Encroach Param= -1, 0, 0, 0
BEGIN DESCRIPTION:
Multiple Run
END DESCRIPTION:

--- Sweetwater Creek Trib 31.f01 (steady flow) ---

Flow Title=Multiple
Number of Profiles=7
Profile Names=10-year,25-year,50-year,1pct_min,100-year,1pct_plu,500-year
River Rch & RM= Sweetwater Creek,Reach-1,4489
     173     237     289     176     350     699     520
Boundary for River Rch & Prof#=Sweetwater Creek,Reach-1,1
Up Type=0
Dn Type=3
Dn Slope=0.005
Boundary for River Rch & Prof#=Sweetwater Creek,Reach-1,2
Up Type=0
Dn Type=3
Dn Slope=0.005
Boundary for River Rch & Prof#=Sweetwater Creek,Reach-1,3
Up Type=0
Dn Type=3
Dn Slope=0.005
Boundary for River Rch & Prof#=Sweetwater Creek,Reach-1,4
Up Type=0
Dn Type=3
Dn Slope=0.005
Boundary for River Rch & Prof#=Sweetwater Creek,Reach-1,5
Up Type=0
Dn Type=3
Dn Slope=0.005
Boundary for River Rch & Prof#=Sweetwater Creek,Reach-1,6
Up Type=0
Dn Type=3
Dn Slope=0.005
Boundary for River Rch & Prof#=Sweetwater Creek,Reach-1,7
Up Type=0
Dn Type=3
Dn Slope=0.005

--- Sweetwater Creek Trib 31.g01 (geometry) ---

Geom Title=Existing Conditions

River Reach=Sweetwater Creek,Reach-1
Reach XY= 30
      1412105.00      6878988.00      1412188.63      6878955.04
      1412263.14      6878781.94      1412449.17      6878590.30
      1412608.61      6878089.50      1412847.14      6877844.17
      1412865.51      6877728.19      1413102.58      6877543.54
      1413211.17      6877530.14      1413411.05      6877339.58
      1413551.67      6877429.99      1413604.90      6877395.81
      1413665.43      6877436.63      1413818.84      6877438.50
      1413995.13      6877338.88      1414161.43      6877395.79
      1414216.84      6877486.34      1414344.55      6877489.39
      1414405.10      6877530.20      1414458.24      6877496.24
      1414557.54      6877543.70      1414651.24      6877689.56
      1414657.27      6877832.06      1414703.73      6877897.71
      1414662.31      6878038.11      1414684.03      6878068.10
      1414773.27      6878138.07      1415003.72      6878091.37
      1415151.59      6878280.42      1415255.00      6878238.00

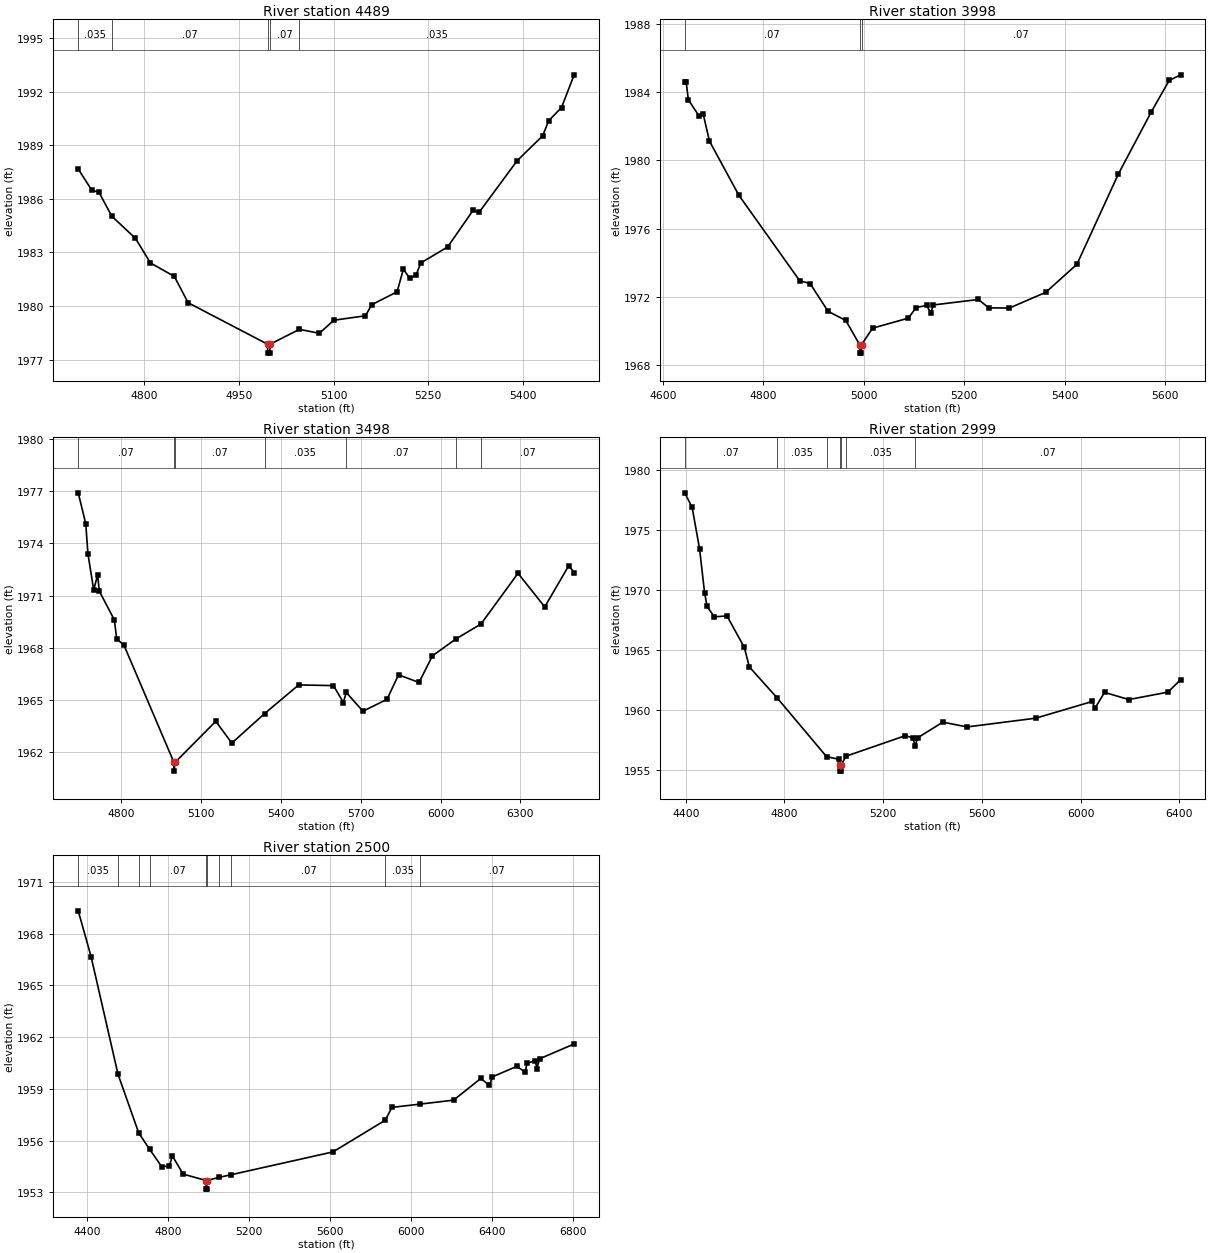
Type RM Length L Ch R = 1,4489,491,491,491
BEGIN DESCRIPTION:
Sweetwater Creek Trib 31 7.0
END DESCRIPTION:
XS GIS Cut Line= 3
      1412505.01      6878938.02      1412385.07      6878658.03
      1411905.01      6878688.00
#Sta/Elev= 30
  4695.4 1987.67  4717.2 1986.47  4728.1 1986.38  4748.6 1985.03  4786.1 1983.79
  4809.7 1982.42  4847.7 1981.66  4869.5 1980.19  4995.3 1977.87  4995.5 1977.37
  4999.0 1977.37  4999.3 1977.87  5045.9 1978.70  5077.5 1978.48  5100.3 1979.21
  5150.4 1979.46  5160.4 1980.08  5200.5 1980.80  5210.5 1982.07  5220.5 1981.55
  5230.5 1981.72  5237.9 1982.41  5280.6 1983.31  5320.7 1985.35  5330.7 1985.26
  5390.8 1988.14  5430.9 1989.52  5440.9 1990.38  5461.0 1991.11  5481.0 1992.94
#Mann=5,-1,0
  4695.4   0.035       0  4748.6    0.07       0  4995.3    0.07       0
  4999.3    0.07       0  5045.9   0.035       0
Bank Sta=4995.3,4999.3
Exp/Cntr=0.3,0.1

Type RM Length L Ch R = 1,3998,500,500,500
BEGIN DESCRIPTION:
Sweetwater Creek Trib 31 6.0
END DESCRIPTION:
XS GIS Cut Line= 3
      1412854.99      6878437.99      1412565.89      6878228.37
      1411955.00      6878388.00
#Sta/Elev= 30
  4642.9 1984.58  4646.0 1984.58  4650.2 1983.55  4671.1 1982.62  4679.6 1982.74
  4692.3 1981.13  4750.7 1977.97  4872.1 1972.96  4893.0 1972.79  4928.6 1971.17
  4964.1 1970.63  4991.5 1969.22  4991.8 1968.72  4995.3 1968.72  4995.5 1969.22
  5017.4 1970.18  5088.8 1970.77  5104.3 1971.39  5124.9 1971.51  5133.5 1971.09
  5138.7 1971.54  5228.3 1971.86  5249.0 1971.37  5290.2 1971.36  5362.7 1972.28
  5424.7 1973.92  5507.4 1979.21  5573.3 1982.86  5608.6 1984.68  5631.4 1985.01
#Mann=3,-1,0
  4642.9    0.07       0  4991.5    0.07       0  4995.5    0.07       0
Bank Sta=4991.5,4995.5
Exp/Cntr=0.3,0.1

Type RM Length L Ch R = 1,3498,499,499,499
BEGIN DESCRIPTION:
Sweetwater Creek Trib 31 5.0
END DESCRIPTION:
XS GIS Cut Line= 3
      1413055.03      6878138.04      1412849.48      6877840.43
      1411355.04      6877988.00
#Sta/Elev= 30
  4638.3 1976.90  4666.7 1975.12  4674.8 1973.40  4696.5 1971.32  4711.3 1972.19
  4717.4 1971.26  4774.2 1969.60  4783.0 1968.51  4810.0 1968.16  4998.0 1961.42
  4998.3 1960.92  5002.0 1961.42  5155.2 1963.78  5215.5 1962.53  5338.3 1964.22
  5466.7 1965.87  5597.4 1965.83  5634.7 1964.86  5645.3 1965.44  5707.9 1964.36
  5798.3 1965.04  5841.9 1966.45  5918.9 1966.01  5969.2 1967.54  6056.5 1968.50
  6151.8 1969.37  6290.7 1972.28  6391.2 1970.35  6481.6 1972.72  6501.7 1972.32
#Mann=7,-1,0
  4638.3    0.07       0  4998.0    0.07       0  5002.0    0.07       0
  5338.3   0.035       0  5645.3    0.07       0  6056.5   0.035       0
  6151.8    0.07       0
Bank Sta=4998,5002
Exp/Cntr=0.3,0.1

Type RM Length L Ch R = 1,2999,499,499,499
BEGIN DESCRIPTION:
Sweetwater Creek Trib 31 4.0
END DESCRIPTION:
XS GIS Cut Line= 3
      1413104.99      6878138.04      1413177.79      6877538.14
      1411805.01      6877238.00
#Sta/Elev= 30
  4395.7 1978.08  4426.0 1976.87  4456.2 1973.39  4476.3 1969.76  4486.4 1968.62
  4515.9 1967.75  4567.0 1967.83  4637.5 1965.20  4657.6 1963.58  4770.8 1960.99
  4970.8 1956.10  5021.1 1955.89  5024.3 1955.40  5024.5 1954.90  5028.0 1954.90
  5028.3 1955.40  5050.2 1956.15  5289.5 1957.85  5320.2 1957.68  5329.2 1957.02
  5340.6 1957.69  5441.7 1958.98  5539.7 1958.58  5818.3 1959.31  6046.9 1960.70
  6058.2 1960.14  6097.0 1961.46  6195.0 1960.86  6354.0 1961.48  6405.2 1962.52
#Mann=7,-1,0
  4395.7    0.07       0  4770.8   0.035       0  4970.8    0.07       0
  5024.3    0.07       0  5028.3    0.07       0  5050.2   0.035       0
  5329.2    0.07       0
Bank Sta=5024.3,5028.3
Exp/Cntr=0.3,0.1

Type RM Length L Ch R = 1,2500,0,0,0
BEGIN DESCRIPTION:
Sweetwater Creek Trib 31 249
END DESCRIPTION:
XS GIS Cut Line= 3
      1413354.99      6878038.02      1413561.66      6877428.39
      1412204.98      6876237.98
#Sta/Elev= 30
  4356.3 1969.32  4419.7 1966.67  4552.6 1959.85  4655.0 1956.44  4708.3 1955.50
  4768.1 1954.49  4806.5 1954.51  4820.9 1955.11  4874.6 1954.05  4987.7 1953.68
  4988.0 1953.18  4991.5 1953.18  4991.7 1953.68  5051.2 1953.86  5113.0 1954.02
  5614.4 1955.34  5872.7 1957.18  5904.8 1957.92  6044.1 1958.11  6209.4 1958.34
  6344.2 1959.60  6386.9 1959.19  6401.1 1959.69  6521.6 1960.30  6564.3 1959.96
  6571.0 1960.47  6613.7 1960.63  6620.3 1960.16  6634.5 1960.74  6804.9 1961.60
#Mann=10,-1,0
  4356.3   0.035       0  4552.6    0.07       0  4655.0   0.035       0
  4708.3    0.07       0  4987.7    0.07       0  4991.7    0.07       0
  5051.2   0.035       0  5113.0    0.07       0  5872.7   0.035       0
  6044.1    0.07       0
Bank Sta=4987.7,4991.7
Exp/Cntr=0.3,0.1

Chan Stop Cuts=-1