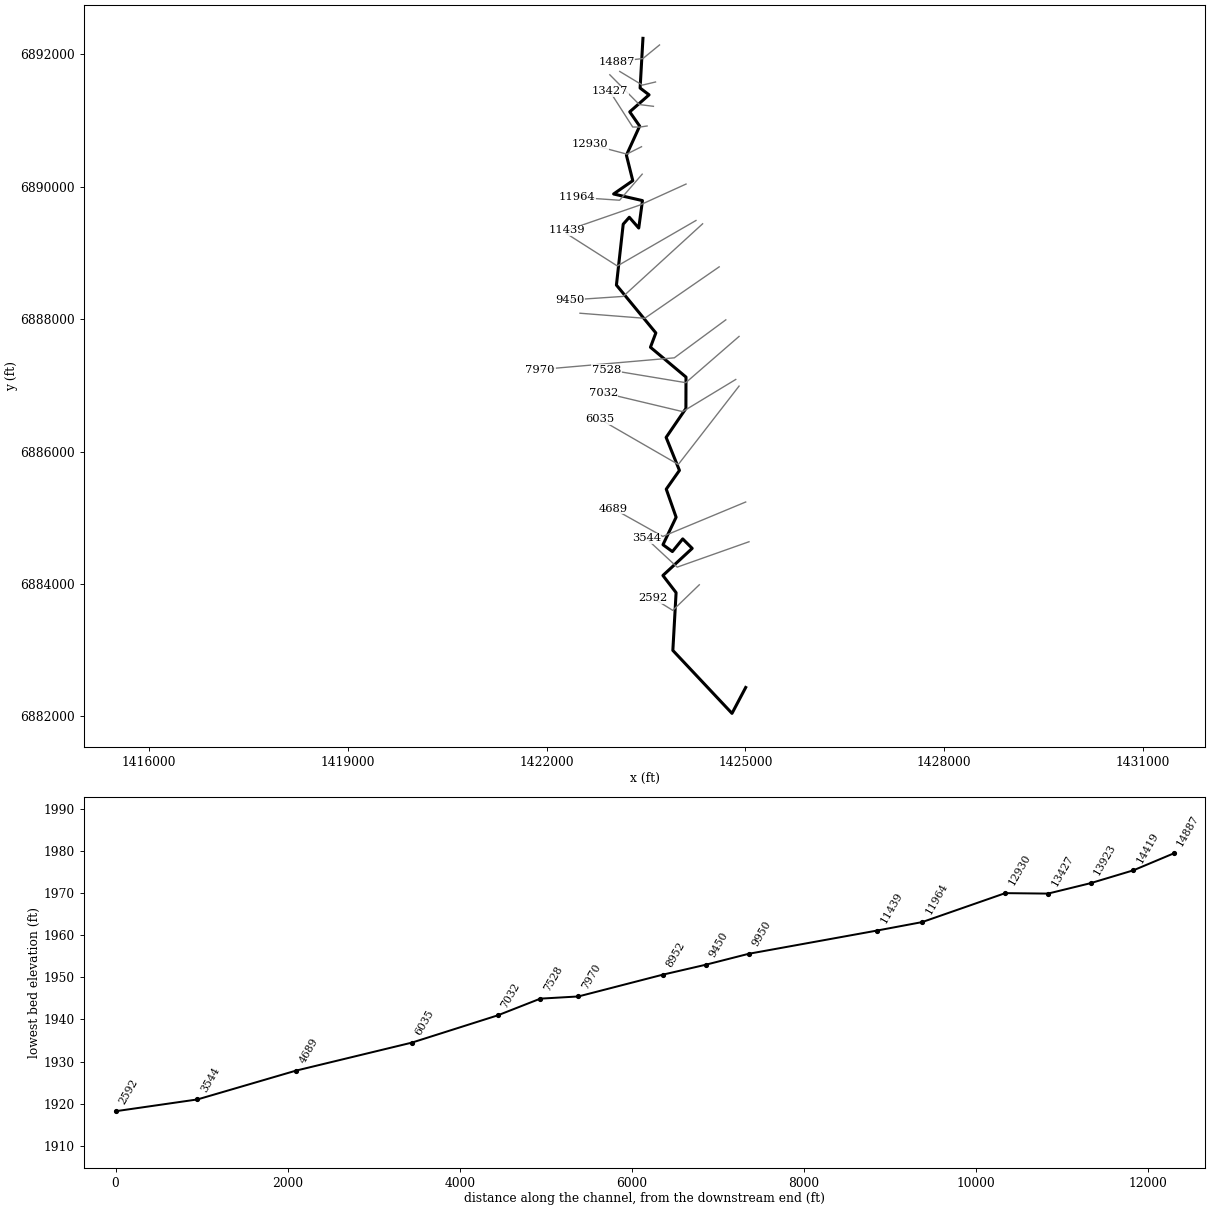
--- Sweetwater Creek Trib 33.prj (project) ---

Proj Title=Sweetwater Creek Trib 33 Base Level Engineering
Current Plan=p01
Default Exp/Contr=0.3,0.1
English Units
Geom File=g01
Flow File=f01
Plan File=p01
BEGIN DESCRIPTION:
Sweetwater Creek Trib 33
END DESCRIPTION:

--- Sweetwater Creek Trib 33.p01 (plan) ---

Plan Title=Multiple Run
Short Identifier=Multiple
Geom File=g01
Flow File=f01
Subcritical Flow
K Sum by GR= 0
Std Step Tol= 0.01
Critical Tol= 0.01
Num of Std Step Trials= 20
Max Error Tol= 0.3
Flow Tol Ratio= 0.001
Split Flow NTrial= 30
Split Flow Tol= 0.02
Split Flow Ratio= 0.02
Log Output Level= 0
Friction Slope Method= 1
Unsteady Friction Slope Method= 2
Unsteady Bridges Friction Slope Method= 1
Parabolic Critical Depth
Global Vel Dist=  1 , 1 , 1
Global Log Level= 0
CheckData=True
Encroach Param= -1, 0, 0, 0
BEGIN DESCRIPTION:
Multiple Run
END DESCRIPTION:

--- Sweetwater Creek Trib 33.f01 (steady flow) ---

Flow Title=Multiple
Number of Profiles=7
Profile Names=10-year,25-year,50-year,1pct_min,100-year,1pct_plu,500-year
River Rch & RM= Sweetwater Creek,Reach-1,14887
     332     478     604     380     757    1511    1206
River Rch & RM= Sweetwater Creek,Reach-1,14419
     428     620     785     493     984    1964    1569
River Rch & RM= Sweetwater Creek,Reach-1,7970
     526     766     972     613    1222    2438    1958
Boundary for River Rch & Prof#=Sweetwater Creek,Reach-1,1
Up Type=0
Dn Type=3
Dn Slope=0.005
Boundary for River Rch & Prof#=Sweetwater Creek,Reach-1,2
Up Type=0
Dn Type=3
Dn Slope=0.005
Boundary for River Rch & Prof#=Sweetwater Creek,Reach-1,3
Up Type=0
Dn Type=3
Dn Slope=0.005
Boundary for River Rch & Prof#=Sweetwater Creek,Reach-1,4
Up Type=0
Dn Type=3
Dn Slope=0.005
Boundary for River Rch & Prof#=Sweetwater Creek,Reach-1,5
Up Type=0
Dn Type=3
Dn Slope=0.005
Boundary for River Rch & Prof#=Sweetwater Creek,Reach-1,6
Up Type=0
Dn Type=3
Dn Slope=0.005
Boundary for River Rch & Prof#=Sweetwater Creek,Reach-1,7
Up Type=0
Dn Type=3
Dn Slope=0.005

--- Sweetwater Creek Trib 33.g01 (geometry) ---

Geom Title=Existing Conditions

River Reach=Sweetwater Creek,Reach-1
Reach XY= 30
      1423455.00      6892238.00      1423412.20      6891487.70
      1423547.21      6891384.96      1423255.69      6891128.17
      1423405.43      6890913.00      1423205.53      6890474.03
      1423301.57      6890089.22      1423012.08      6889887.99
      1423447.78      6889788.35      1423391.60      6889373.82
      1423249.18      6889536.55      1423157.23      6889432.10
      1423054.79      6888512.91      1423649.54      6887790.44
      1423568.20      6887574.35      1424104.44      6887124.02
      1424103.08      6886649.95      1423804.64      6886213.20
      1424005.59      6885715.21      1423806.66      6885431.95
      1423955.41      6885008.13      1423757.17      6884593.43
      1423899.13      6884489.50      1424054.99      6884680.93
      1424197.92      6884538.01      1423756.11      6884128.57
      1423955.02      6883869.59      1423906.14      6882997.43
      1424798.51      6882046.88      1425005.00      6882438.00

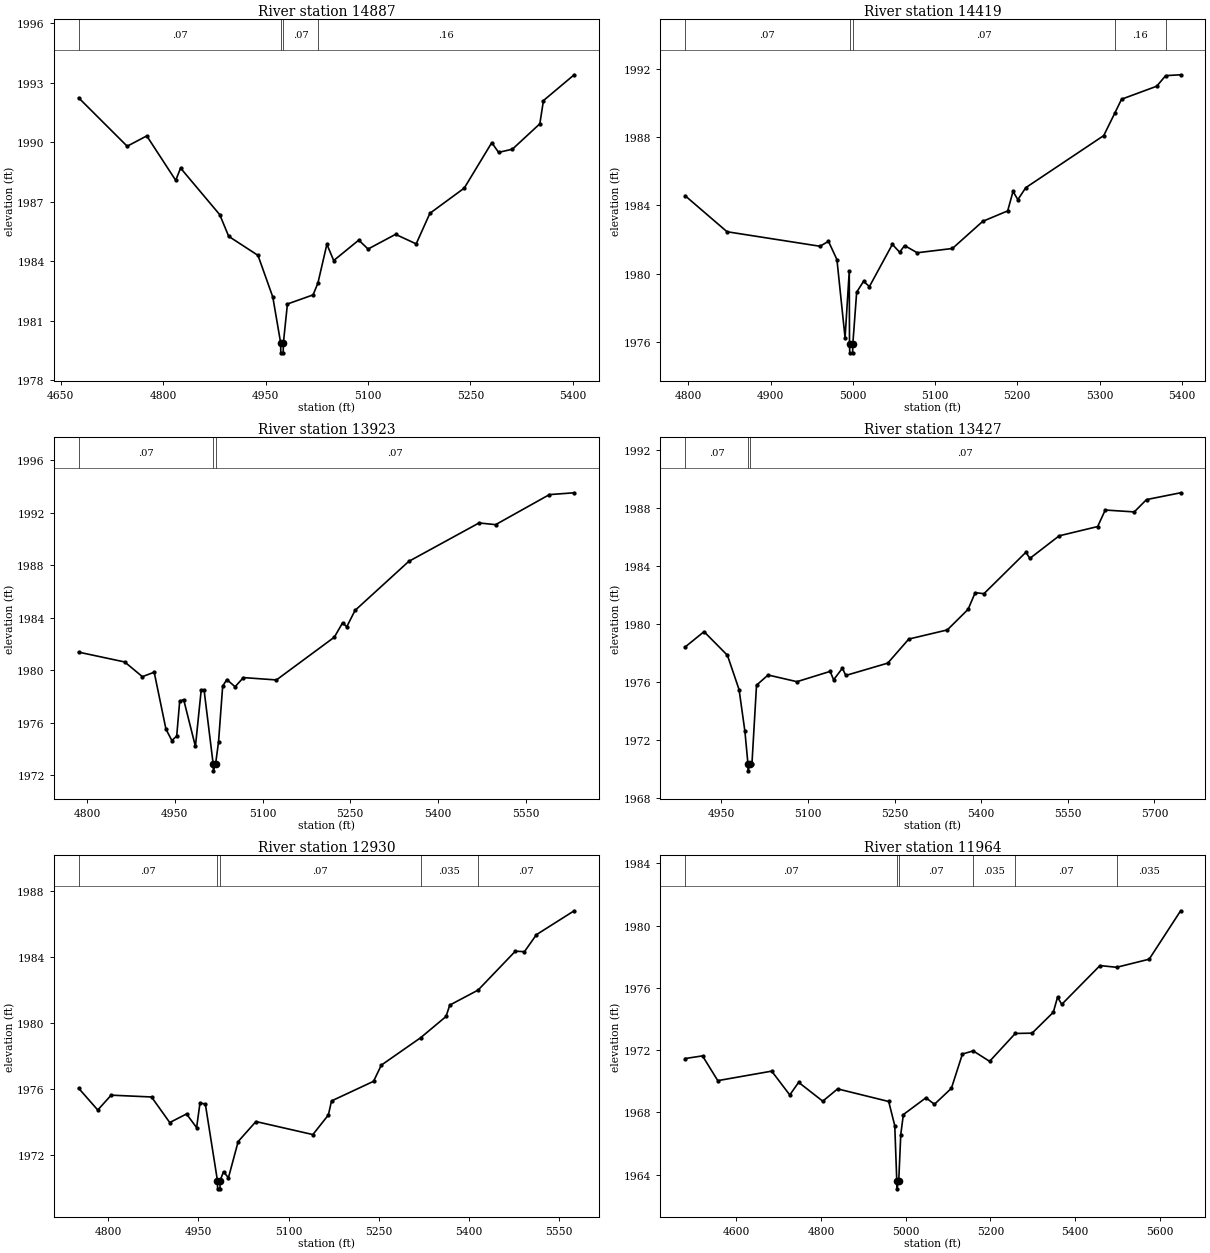
Type RM Length L Ch R = 1,14887,468,468,468
BEGIN DESCRIPTION:
Sweetwater Creek Trib 33 17.0
END DESCRIPTION:
XS GIS Cut Line= 3
      1423705.00      6892138.00      1423454.52      6891932.80
      1423055.03      6891888.00
#Sta/Elev= 30
  4676.2 1992.23  4747.3 1989.79  4776.0 1990.31  4818.4 1988.07  4825.5 1988.69
  4882.9 1986.34  4896.0 1985.25  4938.9 1984.29  4960.6 1982.19  4972.1 1979.88
  4972.3 1979.38  4975.8 1979.38  4976.1 1979.88  4982.0 1981.84  5019.6 1982.30
  5026.7 1982.90  5039.8 1984.85  5049.8 1984.03  5086.5 1985.06  5100.1 1984.61
  5140.4 1985.35  5170.6 1984.87  5190.7 1986.41  5241.0 1987.68  5281.3 1989.97
  5291.3 1989.48  5311.5 1989.64  5351.7 1990.92  5357.0 1992.09  5402.0 1993.39
#Mann=4,-1,0
  4676.2    0.07       0  4972.1    0.07       0  4976.1    0.07       0
  5026.7    0.16       0
Bank Sta=4972.1,4976.1
Exp/Cntr=0.3,0.1

Type RM Length L Ch R = 1,14419,496,496,496
BEGIN DESCRIPTION:
Sweetwater Creek Trib 33 16.0
END DESCRIPTION:
XS GIS Cut Line= 3
      1423644.60      6891578.93      1423446.19      6891531.93
      1423105.00      6891738.00
#Sta/Elev= 30
  4796.1 1984.57  4847.1 1982.46  4960.1 1981.61  4970.4 1981.90  4980.7 1980.83
  4990.6 1976.25  4995.7 1980.15  4996.0 1975.87  4996.3 1975.37  4999.8 1975.37
  5000.0 1975.87  5004.7 1978.92  5013.1 1979.56  5020.2 1979.25  5048.1 1981.72
  5057.0 1981.26  5062.9 1981.65  5078.4 1981.23  5121.1 1981.48  5158.0 1983.07
  5188.3 1983.68  5194.8 1984.82  5200.7 1984.34  5210.3 1985.04  5305.1 1988.09
  5318.6 1989.41  5326.8 1990.22  5369.5 1990.98  5380.4 1991.60  5398.6 1991.65
#Mann=5,-1,0
  4796.1    0.07       0  4996.0    0.07       0  5000.0    0.07       0
  5318.6    0.16       0  5380.4    0.07       0
Bank Sta=4996,5000
Exp/Cntr=0.3,0.1

Type RM Length L Ch R = 1,13923,496,496,496
BEGIN DESCRIPTION:
Sweetwater Creek Trib 33 15.0
END DESCRIPTION:
XS GIS Cut Line= 3
      1423613.20      6891211.83      1423400.35      6891238.38
      1422955.03      6891687.97
#Sta/Elev= 30
  4785.5 1981.38  4864.3 1980.63  4894.5 1979.51  4914.7 1979.85  4934.8 1975.51
  4944.9 1974.64  4953.2 1974.98  4958.3 1977.64  4965.1 1977.76  4985.2 1974.19
  4995.1 1978.49  5000.0 1978.49  5015.6 1972.83  5015.9 1972.33  5019.6 1972.83
  5024.7 1974.53  5031.8 1978.79  5038.9 1979.29  5053.0 1978.74  5067.2 1979.44
  5123.7 1979.26  5222.7 1982.52  5236.9 1983.62  5243.9 1983.31  5258.1 1984.56
  5350.0 1988.30  5470.2 1991.23  5498.5 1991.10  5590.4 1993.39  5632.8 1993.53
#Mann=3,-1,0
  4785.5    0.07       0  5015.6    0.07       0  5019.6    0.07       0
Bank Sta=5015.6,5019.6
Exp/Cntr=0.3,0.1

Type RM Length L Ch R = 1,13427,497,497,497
BEGIN DESCRIPTION:
Sweetwater Creek Trib 33 14.0
END DESCRIPTION:
XS GIS Cut Line= 4
      1423517.46      6890914.80      1423405.81      6890898.03
      1423300.14      6890899.43      1422955.03      6891437.96
#Sta/Elev= 30
  4887.1 1978.39  4919.9 1979.45  4960.4 1977.82  4980.6 1975.45  4990.7 1972.57
  4995.9 1970.35  4996.1 1969.85  4999.9 1970.35  5002.9 1970.35  5010.8 1975.76
  5030.8 1976.46  5080.8 1976.00  5138.3 1976.71  5144.3 1976.13  5159.5 1976.93
  5165.4 1976.43  5238.1 1977.28  5274.5 1978.94  5341.2 1979.57  5377.2 1980.99
  5389.5 1982.14  5404.7 1982.07  5477.4 1984.93  5484.1 1984.50  5534.9 1986.06
  5601.6 1986.70  5614.7 1987.84  5665.0 1987.71  5686.2 1988.56  5745.3 1989.03
#Mann=3,-1,0
  4887.1    0.07       0  4995.9    0.07       0  4999.9    0.07       0
Bank Sta=4995.9,4999.9
Exp/Cntr=0.3,0.1

Type RM Length L Ch R = 1,12930,966,966,966
BEGIN DESCRIPTION:
Sweetwater Creek Trib 33 13.0
END DESCRIPTION:
XS GIS Cut Line= 3
      1423433.41      6890601.80      1423210.64      6890490.32
      1422655.03      6890637.99
#Sta/Elev= 30
  4750.9 1976.06  4782.7 1974.74  4805.0 1975.64  4872.1 1975.53  4902.4 1973.98
  4930.3 1974.50  4947.1 1973.67  4952.7 1975.17  4961.6 1975.10  4981.7 1970.46
  4982.0 1969.96  4985.9 1969.96  4986.2 1970.46  4991.8 1971.00  5000.0 1970.63
  5016.2 1972.83  5045.7 1974.04  5140.4 1973.25  5166.2 1974.44  5171.4 1975.29
  5241.3 1976.48  5254.2 1977.46  5319.5 1979.12  5361.8 1980.41  5368.0 1981.10
  5415.1 1982.01  5477.1 1984.37  5492.2 1984.34  5512.1 1985.37  5574.9 1986.82
#Mann=5,-1,0
  4750.9    0.07       0  4981.7    0.07       0  4986.2    0.07       0
  5319.5   0.035       0  5415.1    0.07       0
Bank Sta=4981.7,4986.2
Exp/Cntr=0.3,0.1

Type RM Length L Ch R = 1,11964,525,525,525
BEGIN DESCRIPTION:
Sweetwater Creek Trib 33 12.0
END DESCRIPTION:
XS GIS Cut Line= 3
      1423443.80      6890187.62      1423102.67      6889793.83
      1422454.98      6889838.00
#Sta/Elev= 30
  4479.0 1971.46  4520.1 1971.63  4556.2 1970.04  4683.5 1970.65  4726.2 1969.12
  4747.1 1969.93  4804.1 1968.72  4839.2 1969.51  4959.8 1968.70  4974.1 1967.15
  4978.9 1963.59  4979.2 1963.09  4983.5 1963.59  4988.3 1966.58  4994.4 1967.86
  5047.8 1968.94  5067.8 1968.52  5107.9 1969.55  5133.9 1971.75  5159.3 1971.95
  5198.1 1971.28  5258.7 1973.07  5298.4 1973.09  5348.5 1974.43  5358.5 1975.40
  5368.5 1974.94  5458.7 1977.43  5498.1 1977.32  5574.9 1977.84  5649.2 1980.95
#Mann=6,-1,0
  4479.0    0.07       0  4978.9    0.07       0  4983.5    0.07       0
  5159.3   0.035       0  5258.7    0.07       0  5498.1   0.035       0
Bank Sta=4978.9,4983.5
Exp/Cntr=0.3,0.1

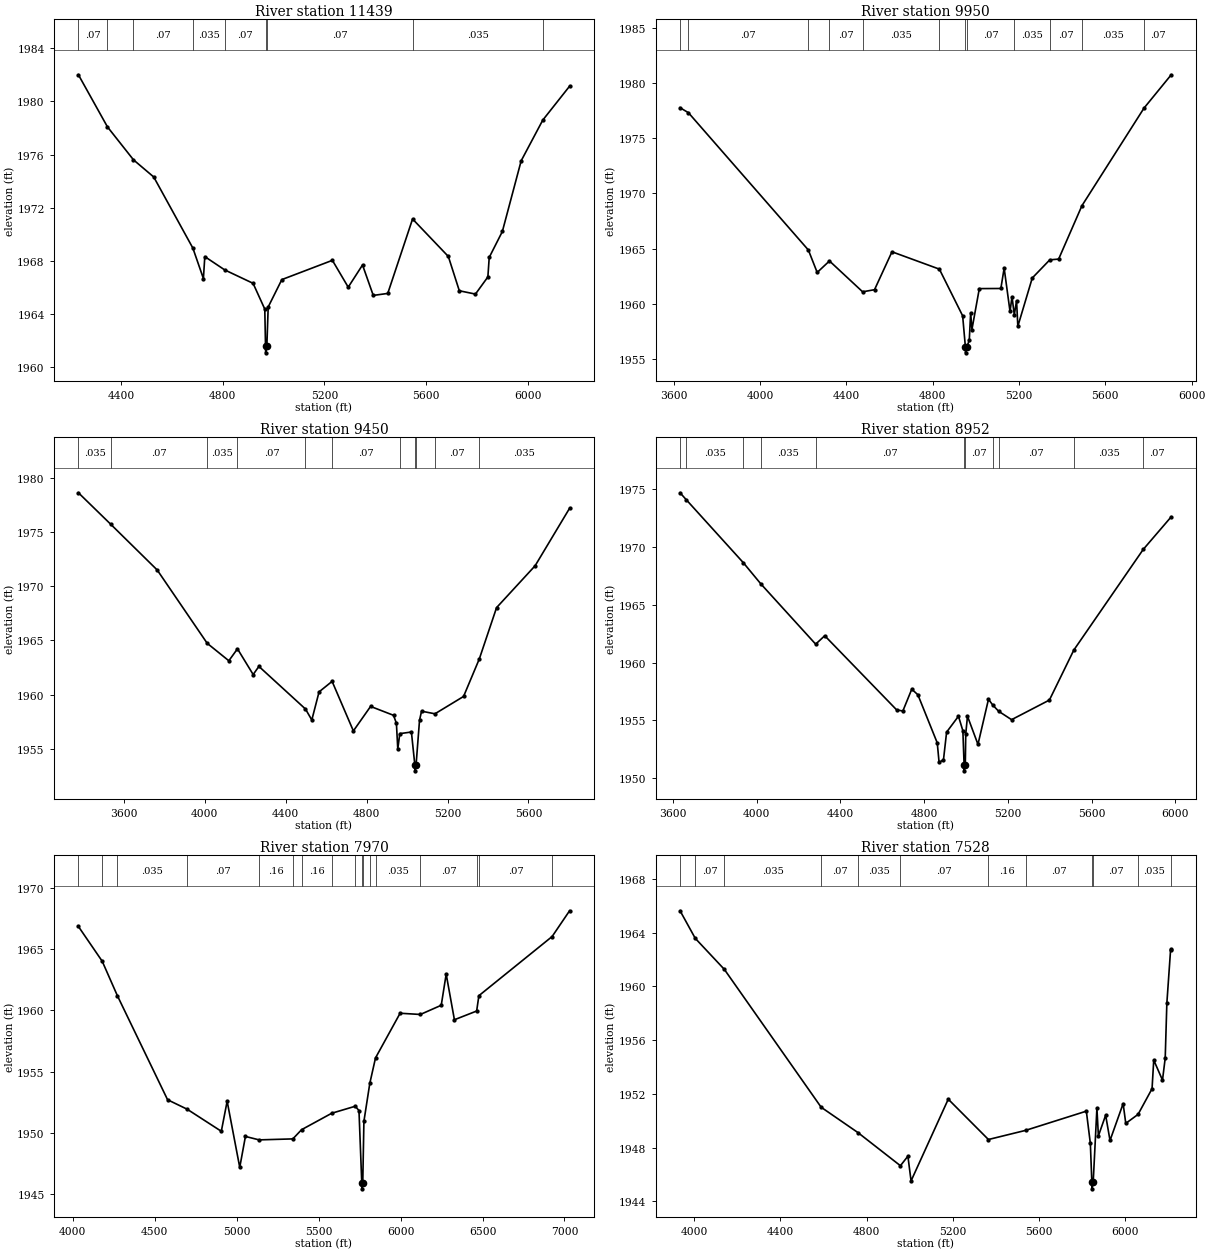
Type RM Length L Ch R = 1,11439,1489,1489,1489
BEGIN DESCRIPTION:
Sweetwater Creek Trib 33 11.0
END DESCRIPTION:
XS GIS Cut Line= 3
      1424104.98      6890037.99      1423405.34      6889719.79
      1422304.99      6889338.00
#Sta/Elev= 30
  4231.4 1982.00  4345.7 1978.08  4448.2 1975.60  4527.9 1974.31  4681.9 1968.96
  4723.4 1966.67  4728.9 1968.32  4807.2 1967.32  4918.9 1966.31  4965.0 1964.37
  4967.9 1961.58  4968.3 1961.08  4973.1 1961.58  4978.4 1964.53  5032.1 1966.59
  5231.1 1968.04  5293.4 1966.02  5349.7 1967.69  5392.0 1965.40  5449.0 1965.55
  5546.7 1971.15  5687.5 1968.33  5730.7 1965.75  5794.2 1965.50  5843.1 1966.79
  5848.4 1968.26  5900.1 1970.21  5974.2 1975.53  6059.2 1978.59  6164.7 1981.14
#Mann=9,-1,0
  4231.4    0.07       0  4345.7   0.035       0  4448.2    0.07       0
  4681.9   0.035       0  4807.2    0.07       0  4967.9    0.07       0
  4973.1    0.07       0  5546.7   0.035       0  6059.2    0.07       0
Bank Sta=4967.9,4973.1
Exp/Cntr=0.3,0.1

Type RM Length L Ch R = 1,9950,500,500,500
BEGIN DESCRIPTION:
Sweetwater Creek Trib 33 10.0
END DESCRIPTION:
XS GIS Cut Line= 3
      1424255.02      6889488.01      1423068.40      6888801.31
      1422305.04      6889287.98
#Sta/Elev= 30
  3629.0 1977.75  3667.7 1977.30  4223.6 1964.88  4264.5 1962.85  4321.4 1963.89
  4475.1 1961.10  4530.2 1961.29  4611.1 1964.72  4830.8 1963.15  4938.6 1958.93
  4951.5 1956.08  4952.0 1955.58  4957.1 1956.08  4969.3 1956.70  4975.8 1959.21
  4981.6 1957.69  5015.9 1961.39  5115.7 1961.40  5131.0 1963.24  5158.2 1959.32
  5167.4 1960.66  5178.0 1959.02  5188.5 1960.30  5194.4 1957.98  5261.3 1962.35
  5342.4 1963.99  5383.5 1964.06  5491.5 1968.89  5779.3 1977.72  5905.3 1980.73
#Mann=12,-1,0
  3629.0   0.035       0  3667.7    0.07       0  4223.6   0.035       0
  4321.4    0.07       0  4475.1   0.035       0  4830.8    0.07       0
  4951.5    0.07       0  4957.1    0.07       0  5178.0   0.035       0
  5342.4    0.07       0  5491.5   0.035       0  5779.3    0.07       0
Bank Sta=4951.5,4957.1
Exp/Cntr=0.3,0.1

Type RM Length L Ch R = 1,9450,498,498,498
BEGIN DESCRIPTION:
Sweetwater Creek Trib 33 9.0
END DESCRIPTION:
XS GIS Cut Line= 3
      1424355.00      6889438.00      1423156.43      6888341.89
      1422355.04      6888288.00
#Sta/Elev= 30
  3375.8 1978.62  3535.9 1975.71  3765.2 1971.50  4012.3 1964.74  4119.2 1963.13
  4161.9 1964.23  4239.5 1961.86  4267.8 1962.61  4498.0 1958.68  4529.3 1957.67
  4565.1 1960.26  4629.6 1961.23  4734.7 1956.66  4819.8 1958.92  4933.2 1958.10
  4947.4 1957.36  4954.2 1954.99  4964.1 1956.41  5021.5 1956.56  5038.7 1953.48
  5039.2 1952.98  5044.4 1953.48  5061.6 1957.64  5071.6 1958.48  5137.9 1958.24
  5279.3 1959.84  5357.3 1963.31  5442.4 1968.03  5632.9 1971.89  5803.2 1977.19
#Mann=11,-1,0
  3375.8   0.035       0  3535.9    0.07       0  4012.3   0.035       0
  4161.9    0.07       0  4498.0   0.035       0  4629.6    0.07       0
  4964.1    0.16       0  5038.7    0.07       0  5044.4    0.16       0
  5137.9    0.07       0  5357.3   0.035       0
Bank Sta=5038.7,5044.4
Exp/Cntr=0.3,0.1

Type RM Length L Ch R = 1,8952,982,982,982
BEGIN DESCRIPTION:
Sweetwater Creek Trib 33 8.0
END DESCRIPTION:
XS GIS Cut Line= 3
      1424605.02      6888788.01      1423481.74      6888011.41
      1422505.04      6888088.00
#Sta/Elev= 30
  3634.4 1974.71  3663.4 1974.12  3936.2 1968.66  4020.1 1966.82  4281.9 1961.60
  4325.2 1962.33  4668.5 1955.91  4698.2 1955.81  4740.7 1957.70  4769.9 1957.22
  4862.5 1953.05  4871.2 1951.36  4892.2 1951.59  4907.1 1953.98  4963.8 1955.36
  4984.8 1954.10  4990.7 1951.13  4991.2 1950.63  4996.4 1951.13  4998.6 1953.84
  5006.8 1955.36  5056.9 1952.92  5107.1 1956.83  5127.4 1956.33  5155.6 1955.79
  5217.4 1955.06  5398.0 1956.76  5514.6 1961.09  5845.8 1969.80  5979.7 1972.63
#Mann=11,-1,0
  3634.4    0.07       0  3663.4   0.035       0  3936.2    0.07       0
  4020.1   0.035       0  4281.9    0.07       0  4990.7    0.07       0
  4996.4    0.07       0  5127.4    0.16       0  5155.6    0.07       0
  5514.6   0.035       0  5845.8    0.07       0
Bank Sta=4990.7,4996.4
Exp/Cntr=0.3,0.1

Type RM Length L Ch R = 1,7970,442,442,442
BEGIN DESCRIPTION:
Sweetwater Creek Trib 33 7.0
END DESCRIPTION:
XS GIS Cut Line= 3
      1424705.03      6887988.03      1423928.34      6887414.67
      1421905.03      6887238.00
#Sta/Elev= 30
  4034.6 1966.84  4179.7 1964.01  4272.3 1961.20  4578.6 1952.72  4697.9 1951.95
  4906.4 1950.15  4942.0 1952.60  5018.8 1947.21  5053.5 1949.73  5136.8 1949.45
  5342.6 1949.53  5396.1 1950.28  5579.9 1951.62  5723.3 1952.19  5746.2 1951.84
  5763.2 1945.96  5763.7 1945.46  5769.3 1945.96  5776.3 1950.96  5812.3 1954.06
  5847.1 1956.13  5997.1 1959.77  6120.7 1959.67  6248.1 1960.42  6278.2 1962.96
  6328.4 1959.24  6464.1 1959.95  6477.7 1961.20  6924.4 1966.02  7031.0 1968.12
#Mann=17,-1,0
  4034.6   0.035       0  4179.7    0.07       0  4272.3   0.035       0
  4697.9    0.07       0  5136.8    0.16       0  5342.6    0.07       0
  5396.1    0.16       0  5579.9    0.07       0  5723.3   0.035       0
  5763.2    0.07       0  5769.3   0.035       0  5812.3    0.07       0
  5847.1   0.035       0  6120.7    0.07       0  6464.1   0.035       0
  6477.7    0.07       0  6924.4   0.035       0
Bank Sta=5763.2,5769.3
Exp/Cntr=0.3,0.1

Type RM Length L Ch R = 1,7528,496,496,496
BEGIN DESCRIPTION:
Sweetwater Creek Trib 33 6.0
END DESCRIPTION:
XS GIS Cut Line= 3
      1424905.00      6887738.00      1424101.06      6887039.50
      1422905.02      6887238.00
#Sta/Elev= 30
  3935.0 1965.63  4005.4 1963.58  4140.3 1961.27  4589.3 1951.01  4759.4 1949.13
  4956.7 1946.66  4991.4 1947.37  5006.1 1945.53  5178.5 1951.61  5364.8 1948.61
  5537.1 1949.29  5818.8 1950.72  5837.4 1948.32  5844.3 1945.44  5844.8 1944.94
  5850.6 1945.44  5867.8 1950.94  5874.7 1948.88  5908.3 1950.42  5928.6 1948.54
  5989.4 1951.28  6001.6 1949.81  6058.6 1950.48  6123.5 1952.39  6131.3 1954.52
  6171.9 1953.03  6184.5 1954.67  6192.1 1958.75  6209.4 1962.72  6212.4 1962.77
#Mann=12,-1,0
  3935.0   0.035       0  4005.4    0.07       0  4140.3   0.035       0
  4589.3    0.07       0  4759.4   0.035       0  4956.7    0.07       0
  5364.8    0.16       0  5537.1    0.07       0  5844.3    0.07       0
  5850.6    0.07       0  6058.6   0.035       0  6209.4    0.07       0
Bank Sta=5844.3,5850.6
Exp/Cntr=0.3,0.1

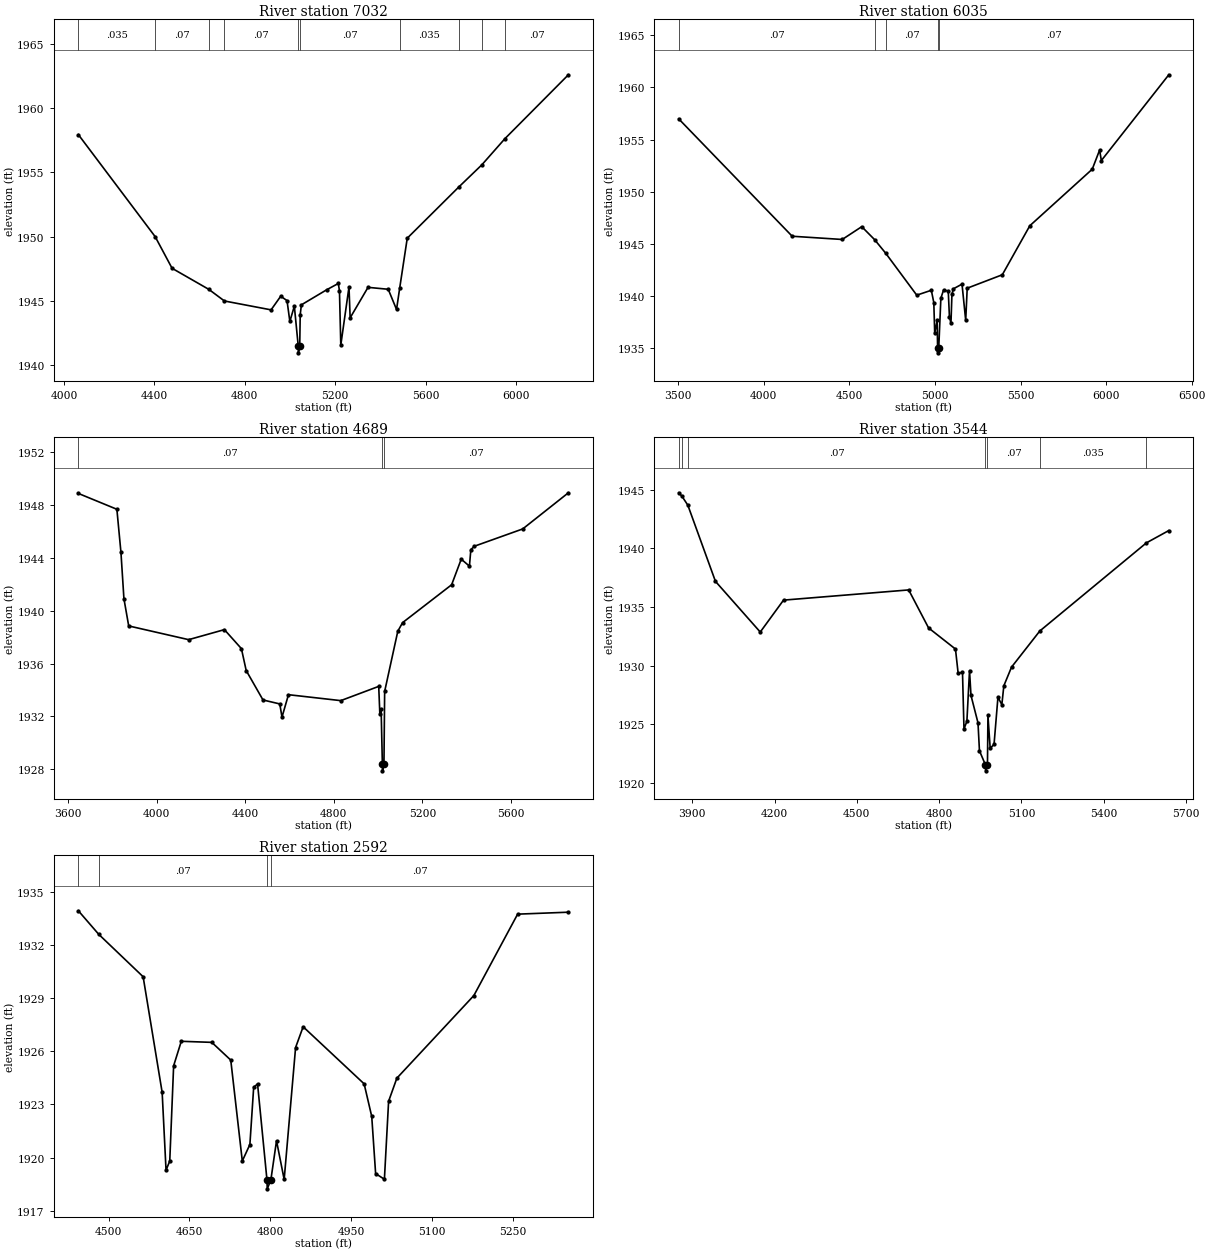
Type RM Length L Ch R = 1,7032,997,997,997
BEGIN DESCRIPTION:
Sweetwater Creek Trib 33 5.0
END DESCRIPTION:
XS GIS Cut Line= 3
      1424854.97      6887087.98      1424053.82      6886602.42
      1422854.97      6886888.01
#Sta/Elev= 30
  4063.2 1957.93  4403.2 1950.00  4478.1 1947.54  4641.0 1945.90  4709.8 1945.00
  4916.3 1944.31  4959.0 1945.37  4986.9 1945.03  4999.4 1943.41  5019.3 1944.60
  5036.7 1941.47  5037.2 1940.97  5043.1 1941.47  5045.3 1943.94  5050.5 1944.70
  5163.3 1945.88  5213.9 1946.36  5219.0 1945.80  5224.9 1941.57  5261.2 1946.09
  5266.3 1943.69  5345.4 1946.06  5434.9 1945.91  5471.7 1944.34  5485.7 1946.01
  5519.1 1949.88  5746.8 1953.85  5849.2 1955.58  5951.7 1957.62  6232.4 1962.58
#Mann=10,-1,0
  4063.2   0.035       0  4403.2    0.07       0  4641.0   0.035       0
  4709.8    0.07       0  5036.7    0.07       0  5043.1    0.07       0
  5485.7   0.035       0  5746.8    0.07       0  5849.2   0.035       0
  5951.7    0.07       0
Bank Sta=5036.7,5043.1
Exp/Cntr=0.3,0.1

Type RM Length L Ch R = 1,6035,1346,1346,1346
BEGIN DESCRIPTION:
Sweetwater Creek Trib 33 4.0
END DESCRIPTION:
XS GIS Cut Line= 3
      1424905.01      6886988.01      1423988.26      6885804.68
      1422804.99      6886488.00
#Sta/Elev= 30
  3503.1 1956.98  4165.8 1945.71  4458.2 1945.40  4572.3 1946.63  4647.0 1945.39
  4711.7 1944.09  4893.7 1940.05  4978.8 1940.52  4993.3 1939.34  4998.6 1936.40
  5013.1 1937.64  5015.4 1935.01  5015.9 1934.51  5022.3 1935.01  5034.6 1939.76
  5050.0 1940.53  5077.7 1940.45  5084.6 1937.97  5093.5 1937.34  5099.3 1940.14
  5107.7 1940.66  5158.1 1941.11  5179.7 1937.63  5188.5 1940.72  5393.6 1942.01
  5554.4 1946.72  5919.1 1952.15  5962.2 1953.99  5972.2 1952.98  6366.4 1961.22
#Mann=5,-1,0
  3503.1    0.07       0  4647.0    0.16       0  4711.7    0.07       0
  5015.4    0.07       0  5022.3    0.07       0
Bank Sta=5015.4,5022.3
Exp/Cntr=0.3,0.1

Type RM Length L Ch R = 1,4689,1145,1145,1145
BEGIN DESCRIPTION:
Sweetwater Creek Trib 33 3.0
END DESCRIPTION:
XS GIS Cut Line= 3
      1425005.01      6885238.00      1423754.93      6884718.03
      1423005.02      6885137.99
#Sta/Elev= 30
  3646.1 1948.89  3820.1 1947.69  3838.5 1944.42  3851.9 1940.92  3873.5 1938.85
  4144.3 1937.81  4305.7 1938.57  4382.6 1937.13  4404.2 1935.47  4480.1 1933.24
  4555.9 1932.94  4565.9 1931.94  4595.1 1933.64  4831.4 1933.19  5002.8 1934.27
  5007.9 1932.17  5013.6 1932.58  5019.3 1928.37  5019.8 1927.87  5026.4 1928.37
  5029.6 1933.89  5089.0 1938.45  5110.6 1939.10  5332.1 1941.97  5375.5 1943.91
  5412.5 1943.38  5418.9 1944.63  5434.8 1944.89  5653.2 1946.20  5859.5 1948.94
#Mann=3,-1,0
  3646.1    0.07       0  5019.3    0.07       0  5026.4    0.07       0
Bank Sta=5019.3,5026.4
Exp/Cntr=0.3,0.1

Type RM Length L Ch R = 1,3544,952,952,952
BEGIN DESCRIPTION:
Sweetwater Creek Trib 33 2.0
END DESCRIPTION:
XS GIS Cut Line= 3
      1425054.95      6884637.98      1423971.71      6884254.57
      1423505.02      6884687.98
#Sta/Elev= 30
  3850.9 1944.74  3862.7 1944.44  3884.0 1943.68  3984.6 1937.19  4147.9 1932.87
  4232.7 1935.59  4688.9 1936.46  4761.4 1933.22  4859.4 1931.42  4869.2 1929.34
  4885.0 1929.45  4890.4 1924.61  4901.0 1925.26  4910.6 1929.59  4915.9 1927.47
  4941.5 1925.13  4946.8 1922.75  4968.8 1921.54  4969.3 1921.04  4976.0 1921.54
  4977.7 1925.76  4985.9 1922.96  5000.0 1923.30  5014.2 1927.32  5028.4 1926.68
  5035.7 1928.29  5063.7 1929.88  5166.8 1932.96  5555.2 1940.47  5636.9 1941.52
#Mann=7,-1,0
  3850.9    0.07       0  3862.7   0.035       0  3884.0    0.07       0
  4968.8    0.07       0  4976.0    0.07       0  5166.8   0.035       0
  5555.2    0.07       0
Bank Sta=4968.8,4976
Exp/Cntr=0.3,0.1

Type RM Length L Ch R = 1,2592,0,0,0
BEGIN DESCRIPTION:
Sweetwater Creek Trib 33 41
END DESCRIPTION:
XS GIS Cut Line= 3
      1424304.98      6883987.98      1423904.99      6883601.64
      1423604.96      6883788.02
#Sta/Elev= 30
  4443.9 1933.92  4481.8 1932.59  4564.1 1930.20  4599.4 1923.68  4606.6 1919.29
  4613.5 1919.81  4620.7 1925.18  4634.9 1926.56  4691.5 1926.50  4726.7 1925.50
  4748.1 1919.81  4762.2 1920.74  4769.2 1923.96  4776.4 1924.16  4793.9 1918.74
  4794.4 1918.24  4801.1 1918.74  4811.6 1920.95  4825.8 1918.77  4847.0 1926.21
  4861.0 1927.38  4974.2 1924.16  4988.3 1922.32  4995.5 1919.10  5011.8 1918.78
  5019.6 1923.18  5034.9 1924.48  5177.8 1929.14  5259.0 1933.73  5353.2 1933.84
#Mann=4,-1,0
  4443.9   0.035       0  4481.8    0.07       0  4793.9    0.07       0
  4801.1    0.07       0
Bank Sta=4793.9,4801.1
Exp/Cntr=0.3,0.1

Chan Stop Cuts=-1