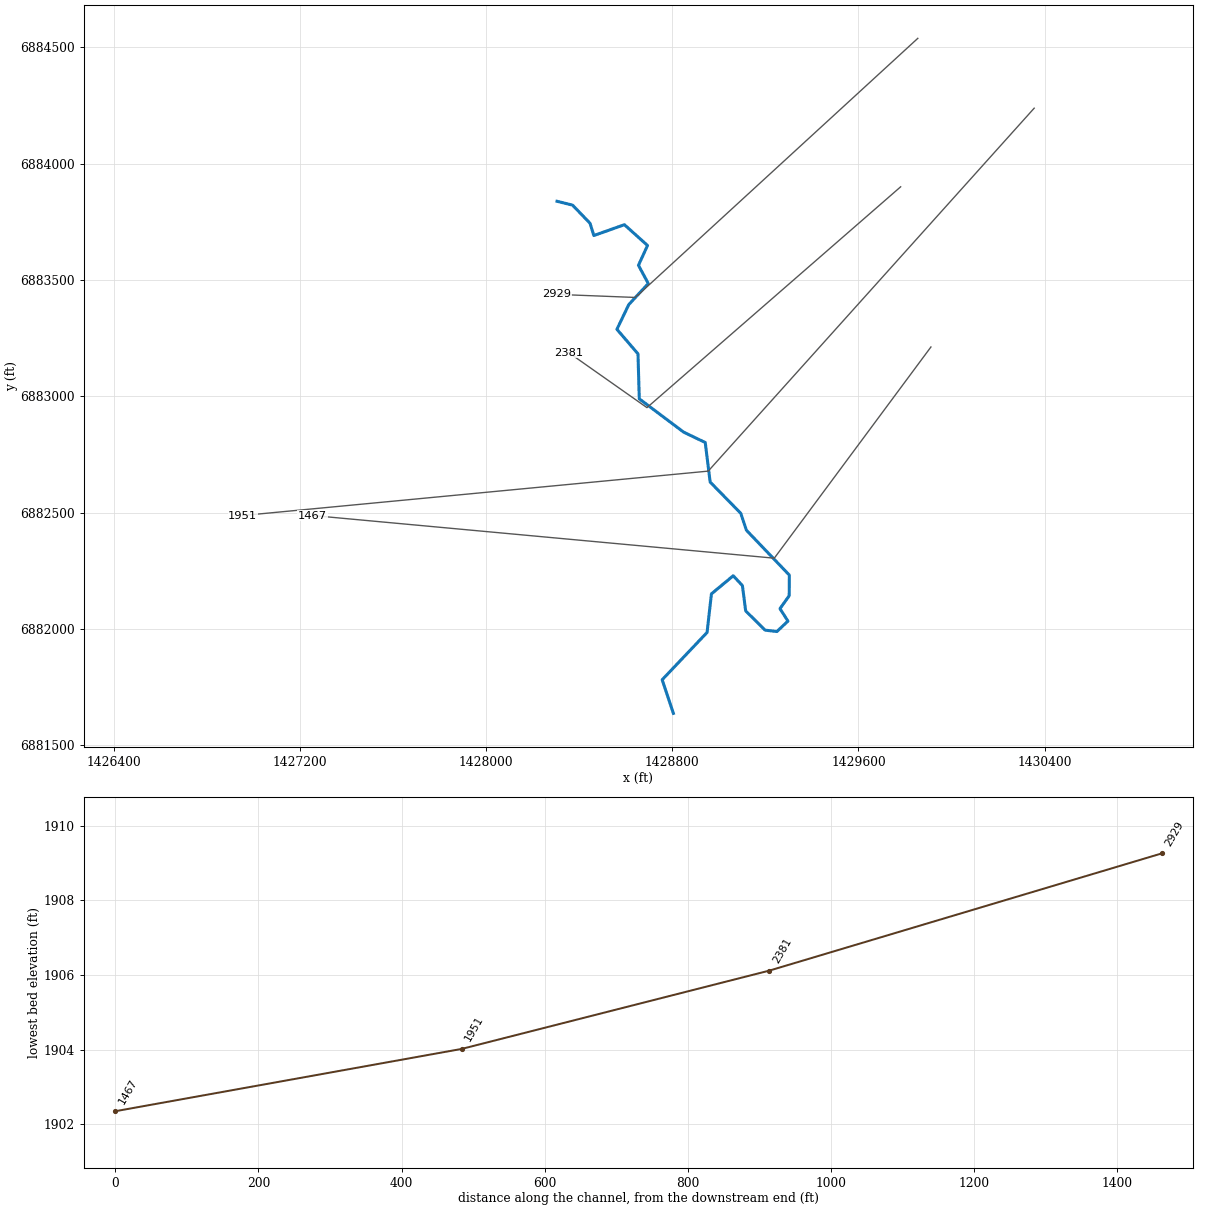
--- Sweetwater Creek Trib 34.prj (project) ---

Proj Title=Sweetwater Creek Trib 34 Base Level Engineering
Current Plan=p01
Default Exp/Contr=0.3,0.1
English Units
Geom File=g01
Flow File=f01
Plan File=p01
BEGIN DESCRIPTION:
Sweetwater Creek Trib 34
END DESCRIPTION:

--- Sweetwater Creek Trib 34.p01 (plan) ---

Plan Title=Multiple Run
Short Identifier=Multiple
Geom File=g01
Flow File=f01
Subcritical Flow
K Sum by GR= 0
Std Step Tol= 0.01
Critical Tol= 0.01
Num of Std Step Trials= 20
Max Error Tol= 0.3
Flow Tol Ratio= 0.001
Split Flow NTrial= 30
Split Flow Tol= 0.02
Split Flow Ratio= 0.02
Log Output Level= 0
Friction Slope Method= 1
Unsteady Friction Slope Method= 2
Unsteady Bridges Friction Slope Method= 1
Parabolic Critical Depth
Global Vel Dist=  1 , 1 , 1
Global Log Level= 0
CheckData=True
Encroach Param= -1, 0, 0, 0
BEGIN DESCRIPTION:
Multiple Run
END DESCRIPTION:

--- Sweetwater Creek Trib 34.f01 (steady flow) ---

Flow Title=Multiple
Number of Profiles=7
Profile Names=10-year,25-year,50-year,1pct_min,100-year,1pct_plu,500-year
River Rch & RM= Sweetwater Creek,Reach-1,2929
     304     430     536     333     664    1324    1029
River Rch & RM= Sweetwater Creek,Reach-1,1951
     391     560     705     440     878    1752    1381
Boundary for River Rch & Prof#=Sweetwater Creek,Reach-1,1
Up Type=0
Dn Type=3
Dn Slope=0.005
Boundary for River Rch & Prof#=Sweetwater Creek,Reach-1,2
Up Type=0
Dn Type=3
Dn Slope=0.005
Boundary for River Rch & Prof#=Sweetwater Creek,Reach-1,3
Up Type=0
Dn Type=3
Dn Slope=0.005
Boundary for River Rch & Prof#=Sweetwater Creek,Reach-1,4
Up Type=0
Dn Type=3
Dn Slope=0.005
Boundary for River Rch & Prof#=Sweetwater Creek,Reach-1,5
Up Type=0
Dn Type=3
Dn Slope=0.005
Boundary for River Rch & Prof#=Sweetwater Creek,Reach-1,6
Up Type=0
Dn Type=3
Dn Slope=0.005
Boundary for River Rch & Prof#=Sweetwater Creek,Reach-1,7
Up Type=0
Dn Type=3
Dn Slope=0.005

--- Sweetwater Creek Trib 34.g01 (geometry) ---

Geom Title=Existing Conditions

River Reach=Sweetwater Creek,Reach-1
Reach XY= 30
      1428305.00      6883838.00      1428371.74      6883821.44
      1428446.73      6883743.66      1428463.19      6883690.80
      1428594.39      6883737.40      1428693.90      6883648.08
      1428654.79      6883563.00      1428697.17      6883484.60
      1428613.16      6883394.05      1428562.30      6883287.92
      1428652.81      6883182.56      1428658.45      6882989.25
      1428848.98      6882846.19      1428941.77      6882801.67
      1428962.82      6882631.81      1429094.22      6882497.68
      1429118.63      6882424.79      1429303.03      6882232.11
      1429302.53      6882143.48      1429262.81      6882087.89
      1429297.11      6882034.34      1429249.76      6881989.69
      1429198.97      6881995.45      1429115.51      6882078.19
      1429101.39      6882186.99      1429061.99      6882229.18
      1428968.37      6882151.38      1428949.53      6881985.55
      1428756.71      6881782.38      1428805.00      6881638.00

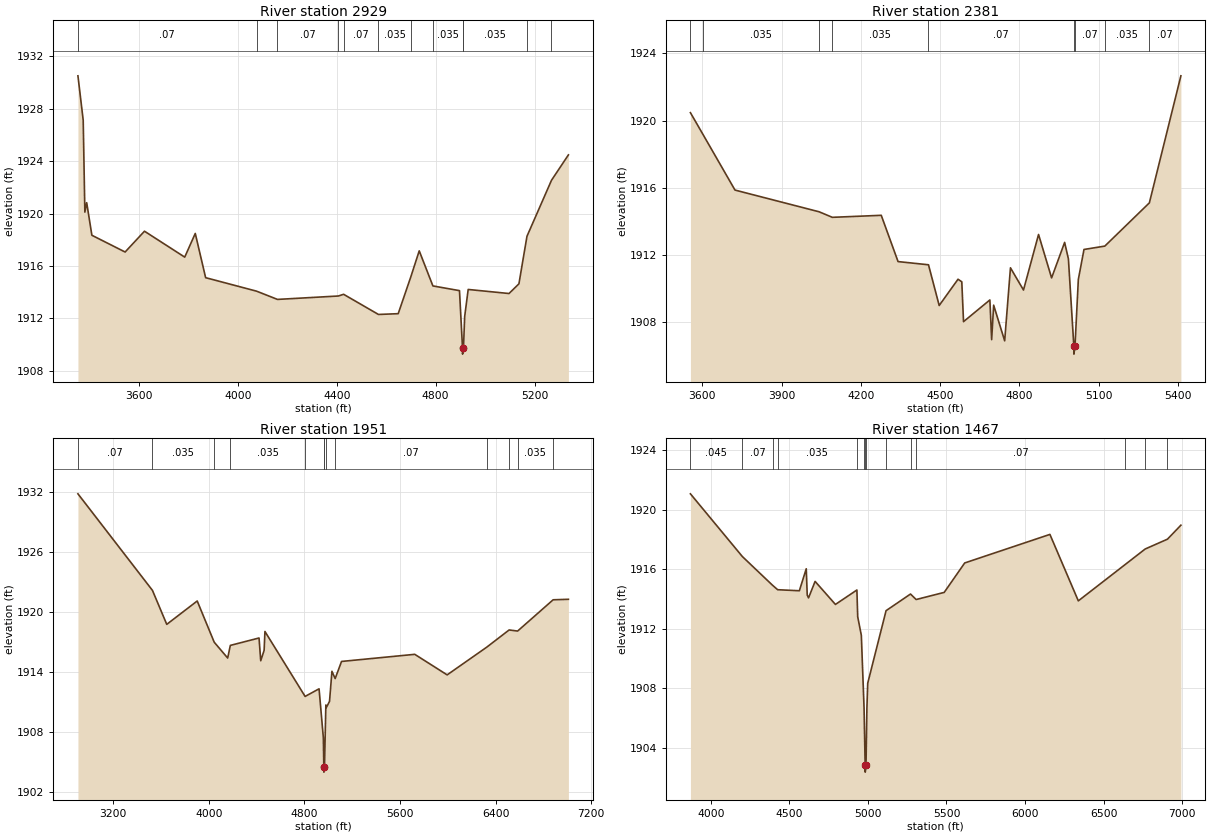
Type RM Length L Ch R = 1,2929,548,548,548
BEGIN DESCRIPTION:
Sweetwater Creek Trib 34 3.0
END DESCRIPTION:
XS GIS Cut Line= 3
      1429854.99      6884537.99      1428641.55      6883424.81
      1428305.01      6883438.00
#Sta/Elev= 30
  3353.3 1930.52  3374.6 1927.13  3381.3 1920.11  3388.7 1920.83  3409.7 1918.34
  3544.1 1917.06  3622.4 1918.65  3785.2 1916.67  3827.8 1918.48  3869.7 1915.10
  4075.6 1914.07  4160.3 1913.44  4406.4 1913.70  4427.7 1913.83  4568.7 1912.29
  4648.5 1912.35  4699.6 1915.17  4733.5 1917.15  4788.8 1914.47  4896.3 1914.11
  4908.5 1909.76  4908.8 1909.26  4912.5 1909.76  4917.3 1912.13  4931.5 1914.20
  5096.6 1913.89  5136.7 1914.63  5169.2 1918.26  5268.4 1922.54  5336.8 1924.48
#Mann=12,-1,0
  3353.3    0.07       0  4075.6   0.035       0  4160.3    0.07       0
  4406.4   0.035       0  4427.7    0.07       0  4568.7   0.035       0
  4699.6    0.07       0  4788.8   0.035       0  4908.5   0.035       0
  4912.5   0.035       0  5169.2    0.07       0  5268.4   0.035       0
Bank Sta=4908.5,4912.5
Exp/Cntr=0.3,0.1

Type RM Length L Ch R = 1,2381,430,430,430
BEGIN DESCRIPTION:
Sweetwater Creek Trib 34 2.0
END DESCRIPTION:
XS GIS Cut Line= 3
      1429781.29      6883900.19      1428691.37      6882951.46
      1428355.01      6883187.99
#Sta/Elev= 30
  3555.0 1920.47  3601.7 1919.20  3723.7 1915.87  4042.0 1914.58  4092.1 1914.25
  4277.2 1914.37  4340.8 1911.62  4456.0 1911.43  4496.5 1909.01  4567.7 1910.57
  4582.0 1910.42  4588.6 1908.05  4688.3 1909.34  4695.0 1906.98  4702.6 1909.03
  4744.3 1906.91  4766.2 1911.25  4815.5 1909.93  4872.5 1913.23  4921.9 1910.65
  4971.2 1912.76  4985.5 1911.78  5006.0 1906.62  5006.3 1906.12  5010.5 1906.62
  5023.1 1910.56  5044.5 1912.34  5123.3 1912.54  5291.9 1915.11  5411.2 1922.66
#Mann=9,-1,0
  3555.0    0.07       0  3601.7   0.035       0  4042.0    0.07       0
  4092.1   0.035       0  4456.0    0.07       0  5006.0    0.07       0
  5010.5    0.07       0  5123.3   0.035       0  5291.9    0.07       0
Bank Sta=5006,5010.5
Exp/Cntr=0.3,0.1

Type RM Length L Ch R = 1,1951,484,484,484
BEGIN DESCRIPTION:
Sweetwater Creek Trib 34 1.0
END DESCRIPTION:
XS GIS Cut Line= 3
      1430354.97      6884237.96      1428954.56      6882678.73
      1426955.03      6882488.00
#Sta/Elev= 30
  2904.2 1931.78  3527.7 1922.15  3647.5 1918.76  3902.4 1921.09  4044.6 1916.98
  4157.3 1915.40  4179.5 1916.66  4419.7 1917.40  4433.9 1915.13  4462.3 1916.17
  4469.1 1918.05  4805.3 1911.57  4922.0 1912.33  4957.9 1907.45  4961.9 1904.52
  4962.3 1904.02  4967.4 1904.52  4978.9 1910.72  4982.7 1910.46  5009.6 1911.08
  5029.7 1914.08  5056.7 1913.35  5110.1 1915.06  5722.8 1915.77  5994.0 1913.72
  6324.8 1916.48  6512.5 1918.20  6583.5 1918.09  6880.8 1921.21  7008.6 1921.26
#Mann=13,-1,0
  2904.2    0.07       0  3527.7   0.035       0  4044.6    0.07       0
  4179.5   0.035       0  4805.3    0.07       0  4961.9    0.07       0
  4967.4    0.07       0  4982.7    0.16       0  5056.7    0.07       0
  6324.8   0.035       0  6512.5    0.07       0  6583.5   0.035       0
  6880.8    0.07       0
Bank Sta=4961.9,4967.4
Exp/Cntr=0.3,0.1

Type RM Length L Ch R = 1,1467,0,0,0
BEGIN DESCRIPTION:
Sweetwater Creek Trib 34 37
END DESCRIPTION:
XS GIS Cut Line= 3
      1429911.37      6883212.11      1429238.43      6882304.71
      1427254.98      6882488.00
#Sta/Elev= 30
  3870.3 1921.07  4201.0 1916.85  4392.9 1914.92  4425.6 1914.62  4563.6 1914.55
  4607.5 1916.03  4613.7 1914.26  4622.1 1914.07  4663.8 1915.18  4793.2 1913.63
  4929.8 1914.60  4935.0 1912.80  4958.1 1911.55  4975.4 1906.68  4982.3 1902.85
  4982.8 1902.35  4987.9 1902.85  4993.5 1906.63  4998.7 1908.33  5115.5 1913.21
  5271.0 1914.33  5307.0 1913.96  5485.5 1914.44  5616.0 1916.42  6158.3 1918.34
  6339.1 1913.87  6635.6 1916.30  6764.9 1917.36  6906.5 1918.02  6991.9 1918.96
#Mann=14,-1,0
  3870.3   0.045       0  4201.0    0.07       0  4392.9   0.045       0
  4425.6   0.035       0  4929.8    0.07       0  4975.4    0.16       0
  4982.3    0.07       0  4987.9    0.16       0  5115.5    0.07       0
  5271.0    0.16       0  5307.0    0.07       0  6635.6   0.035       0
  6764.9    0.07       0  6906.5   0.035       0
Bank Sta=4982.3,4987.9
Exp/Cntr=0.3,0.1

Chan Stop Cuts=-1