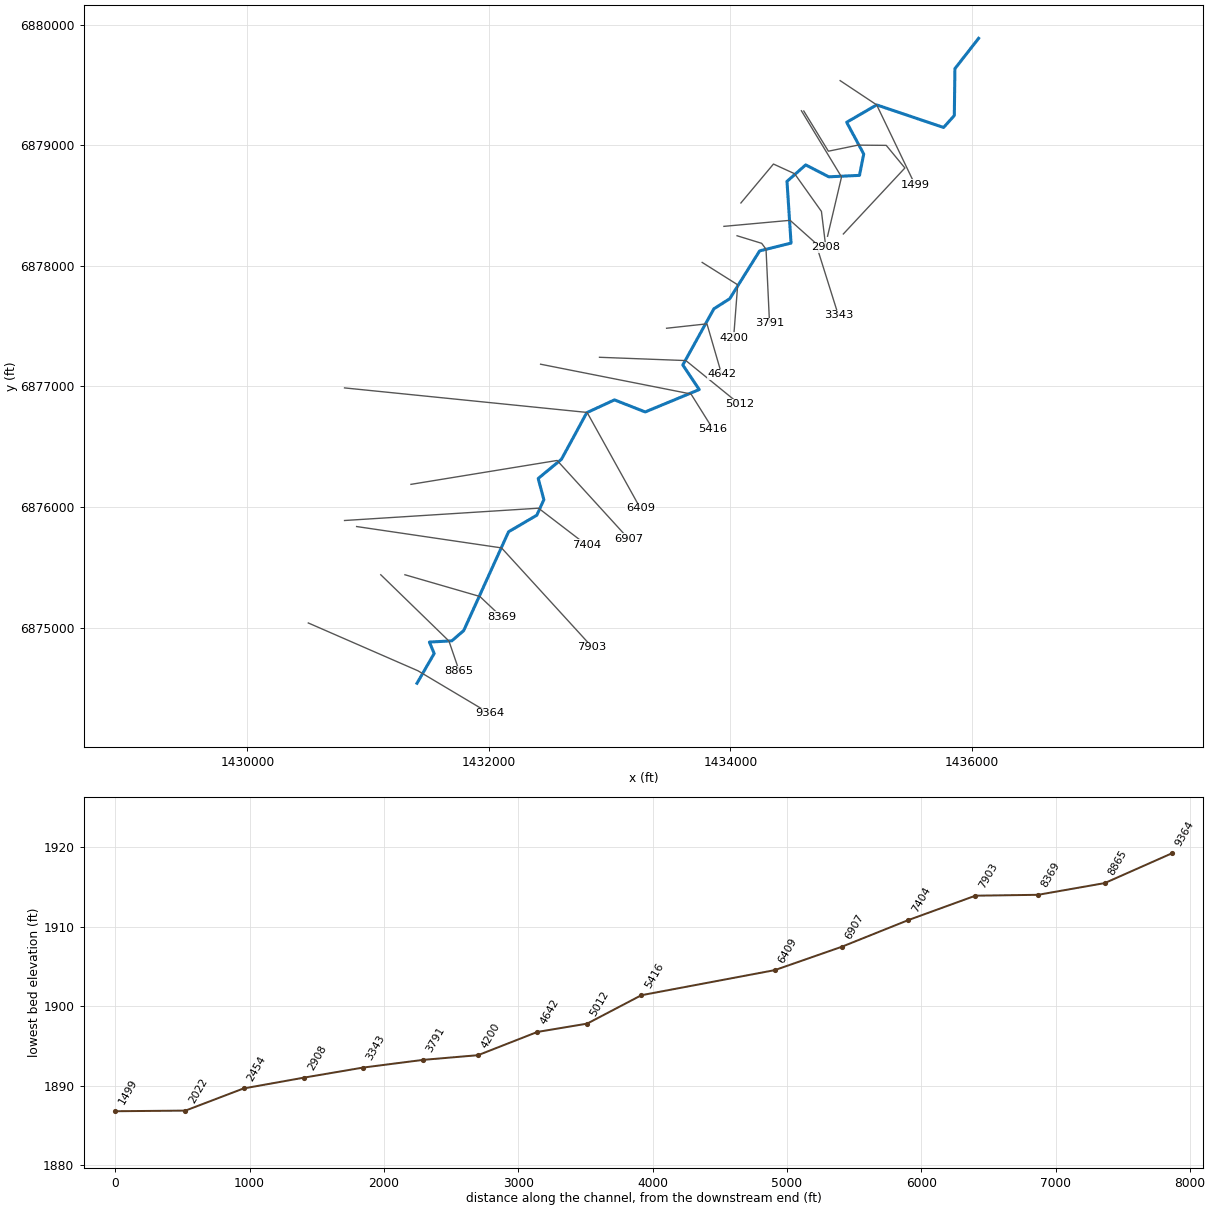
--- Sweetwater Creek Trib 35.prj (project) ---

Proj Title=Sweetwater Creek Trib 35 Base Level Engineering
Current Plan=p01
Default Exp/Contr=0.3,0.1
English Units
Geom File=g01
Flow File=f01
Plan File=p01
Y Axis Title=Elevation
X Axis Title(PF)=Main Channel Distance
X Axis Title(XS)=Station
BEGIN DESCRIPTION:
Sweetwater Creek Trib 35
END DESCRIPTION:
DSS Export Rating Curves= 0
DSS Export Rating Curve Sorted= 0
DSS Export Volume Flow Curves= 0
DXF OffsetX= 0
DXF OffsetY= 0
DXF ScaleX= 1
DXF ScaleY= 10

--- Sweetwater Creek Trib 35.p01 (plan) ---

Plan Title=Multiple Run
Short Identifier=Multiple
Geom File=g01
Flow File=f01
Subcritical Flow
K Sum by GR= 0
Std Step Tol= 0.01
Critical Tol= 0.01
Num of Std Step Trials= 20
Max Error Tol= 0.3
Flow Tol Ratio= 0.001
Split Flow NTrial= 30
Split Flow Tol= 0.02
Split Flow Ratio= 0.02
Log Output Level= 0
Friction Slope Method= 1
Unsteady Friction Slope Method= 2
Unsteady Bridges Friction Slope Method= 1
Parabolic Critical Depth
Global Vel Dist=  1 , 1 , 1
Global Log Level= 0
CheckData=True
Encroach Param= -1, 0, 0, 0
BEGIN DESCRIPTION:
Multiple Run
END DESCRIPTION:

--- Sweetwater Creek Trib 35.f01 (steady flow) ---

Flow Title=Multiple
Number of Profiles=7
Profile Names=10-year,25-year,50-year,1pct_min,100-year,1pct_plu,500-year
River Rch & RM= Sweetwater Creek,Reach-1,9364
     236     328     403     247     493     983     745
River Rch & RM= Sweetwater Creek,Reach-1,7903
     305     429     532     328     654    1306    1003
River Rch & RM= Sweetwater Creek,Reach-1,2454
     424     606     760     473     944    1883    1474
Boundary for River Rch & Prof#=Sweetwater Creek,Reach-1,1
Up Type=0
Dn Type=3
Dn Slope=0.005
Boundary for River Rch & Prof#=Sweetwater Creek,Reach-1,2
Up Type=0
Dn Type=3
Dn Slope=0.005
Boundary for River Rch & Prof#=Sweetwater Creek,Reach-1,3
Up Type=0
Dn Type=3
Dn Slope=0.005
Boundary for River Rch & Prof#=Sweetwater Creek,Reach-1,4
Up Type=0
Dn Type=3
Dn Slope=0.005
Boundary for River Rch & Prof#=Sweetwater Creek,Reach-1,5
Up Type=0
Dn Type=3
Dn Slope=0.005
Boundary for River Rch & Prof#=Sweetwater Creek,Reach-1,6
Up Type=0
Dn Type=3
Dn Slope=0.005
Boundary for River Rch & Prof#=Sweetwater Creek,Reach-1,7
Up Type=0
Dn Type=3
Dn Slope=0.005

--- Sweetwater Creek Trib 35.g01 (geometry) ---

Geom Title=Existing Conditions

River Reach=Sweetwater Creek,Reach-1
Reach XY= 30
      1431405.00      6874538.00      1431547.17      6874784.61
      1431507.67      6874879.55      1431693.53      6874889.74
      1431791.46      6874974.45      1432163.00      6875794.38
      1432396.87      6875931.93      1432455.39      6876060.80
      1432408.46      6876236.50      1432601.33      6876396.19
      1432810.61      6876782.41      1433039.94      6876888.72
      1433294.37      6876788.60      1433741.66      6876974.21
      1433605.70      6877178.16      1433863.03      6877644.34
      1433994.35      6877728.01      1434241.65      6878124.64
      1434501.97      6878189.39      1434468.34      6878701.31
      1434623.29      6878838.08      1434814.59      6878739.21
      1435068.74      6878751.20      1435103.64      6878928.33
      1434962.49      6879191.59      1435210.97      6879335.86
      1435764.81      6879148.42      1435853.80      6879247.58
      1435858.75      6879636.45      1436055.00      6879888.00

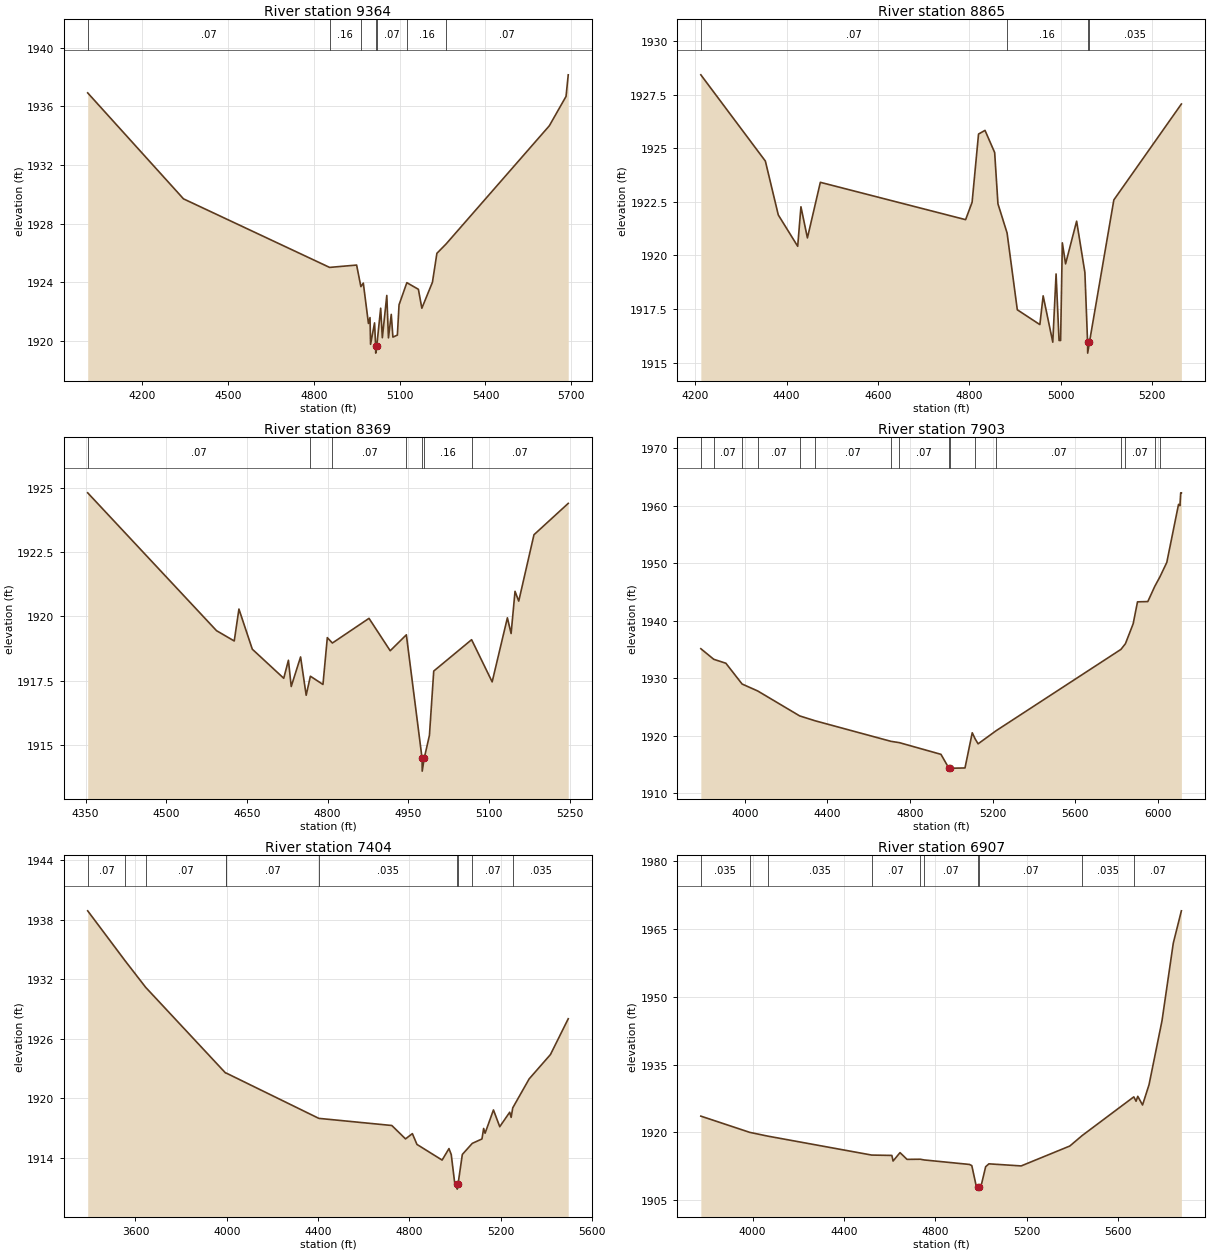
Type RM Length L Ch R = 1,9364,499,499,499
BEGIN DESCRIPTION:
Sweetwater Creek Trib 35 9.0
END DESCRIPTION:
XS GIS Cut Line= 3
      1430505.03      6875037.99      1431412.86      6874641.33
      1432004.96      6874288.02
#Sta/Elev= 30
  4009.3 1936.91  4344.3 1929.69  4855.1 1925.02  4949.6 1925.18  4964.5 1923.71
  4973.0 1923.95  4990.9 1921.20  4996.4 1921.60  4998.4 1919.78  5012.3 1921.24
  5016.1 1919.68  5016.4 1919.18  5020.1 1919.68  5033.7 1922.24  5039.5 1920.23
  5055.1 1923.11  5060.9 1920.22  5070.7 1921.82  5076.5 1920.27  5092.1 1920.41
  5097.9 1922.47  5125.2 1923.98  5165.5 1923.53  5177.7 1922.24  5214.7 1924.01
  5230.3 1925.98  5262.6 1926.62  5623.4 1934.67  5681.8 1936.67  5689.5 1938.14
#Mann=7,-1,0
  4009.3    0.07       0  4855.1    0.16       0  4964.5    0.07       0
  5016.1    0.07       0  5020.1    0.07       0  5125.2    0.16       0
  5262.6    0.07       0
Bank Sta=5016.1,5020.1
Exp/Cntr=0.3,0.1

Type RM Length L Ch R = 1,8865,496,496,496
BEGIN DESCRIPTION:
Sweetwater Creek Trib 35 8.0
END DESCRIPTION:
XS GIS Cut Line= 3
      1431105.03      6875437.97      1431669.38      6874888.30
      1431754.99      6874638.04
#Sta/Elev= 30
  4212.2 1928.42  4353.5 1924.40  4381.8 1921.89  4424.3 1920.43  4431.4 1922.27
  4445.6 1920.82  4473.9 1923.41  4792.0 1921.67  4806.2 1922.48  4820.3 1925.66
  4834.5 1925.83  4855.6 1924.80  4862.8 1922.41  4882.8 1921.05  4905.2 1917.47
  4954.6 1916.78  4961.8 1918.12  4982.9 1915.96  4990.1 1919.14  4996.6 1916.04
  5000.0 1916.04  5003.8 1920.59  5010.9 1919.61  5035.1 1921.60  5053.2 1919.21
  5059.1 1915.95  5059.3 1915.45  5063.1 1915.95  5116.6 1922.59  5264.5 1927.06
#Mann=4,-1,0
  4212.2    0.07       0  4882.8    0.16       0  5059.1    0.07       0
  5063.1   0.035       0
Bank Sta=5059.1,5063.1
Exp/Cntr=0.3,0.1

Type RM Length L Ch R = 1,8369,466,466,466
BEGIN DESCRIPTION:
Sweetwater Creek Trib 35 7.0
END DESCRIPTION:
XS GIS Cut Line= 3
      1431305.03      6875437.99      1431925.40      6875257.83
      1432105.01      6875087.99
#Sta/Elev= 30
  4354.0 1924.80  4593.5 1919.44  4626.4 1919.04  4635.1 1920.28  4660.0 1918.72
  4718.4 1917.59  4727.1 1918.29  4732.3 1917.27  4749.7 1918.42  4760.1 1916.93
  4767.9 1917.67  4791.3 1917.35  4799.4 1919.17  4808.8 1918.96  4876.9 1919.92
  4916.3 1918.66  4946.3 1919.28  4975.5 1914.48  4975.8 1913.98  4979.5 1914.48
  4989.2 1915.37  4997.2 1917.87  5067.6 1919.09  5105.8 1917.45  5134.1 1919.94
  5141.0 1919.33  5148.3 1920.97  5155.2 1920.59  5183.5 1923.17  5247.2 1924.39
#Mann=7,-1,0
  4354.0    0.07       0  4767.9    0.16       0  4808.8    0.07       0
  4946.3    0.16       0  4975.5    0.07       0  4979.5    0.16       0
  5067.6    0.07       0
Bank Sta=4975.5,4979.5
Exp/Cntr=0.3,0.1

Type RM Length L Ch R = 1,7903,499,499,499
BEGIN DESCRIPTION:
Sweetwater Creek Trib 35 6.0
END DESCRIPTION:
XS GIS Cut Line= 3
      1430905.04      6875837.99      1432104.93      6875660.76
      1432854.97      6874838.04
#Sta/Elev= 30
  3787.1 1935.16  3849.6 1933.32  3908.4 1932.63  3986.8 1929.02  4062.4 1927.81
  4265.7 1923.47  4340.9 1922.62  4707.6 1919.05  4748.4 1918.82  4949.5 1916.79
  4988.0 1914.37  4988.2 1913.87  4992.0 1914.37  5065.8 1914.42  5100.9 1920.54
  5115.2 1919.46  5129.3 1918.62  5217.0 1920.91  5821.0 1935.05  5842.5 1936.04
  5879.9 1939.50  5900.9 1943.31  5950.8 1943.36  5984.1 1945.98  6009.6 1947.67
  6042.7 1950.17  6099.5 1960.26  6106.3 1960.03  6110.0 1962.27  6113.3 1962.27
#Mann=16,-1,0
  3787.1   0.035       0  3849.6    0.07       0  3986.8   0.035       0
  4062.4    0.07       0  4265.7    0.16       0  4340.9    0.07       0
  4707.6   0.035       0  4748.4    0.07       0  4988.0    0.07       0
  4992.0    0.07       0  5115.2    0.16       0  5217.0    0.07       0
  5821.0   0.035       0  5842.5    0.07       0  5984.1   0.035       0
  6009.6    0.07       0
Bank Sta=4988,4992
Exp/Cntr=0.3,0.1

Type RM Length L Ch R = 1,7404,497,497,497
BEGIN DESCRIPTION:
Sweetwater Creek Trib 35 5.0
END DESCRIPTION:
XS GIS Cut Line= 3
      1430805.03      6875888.00      1432411.18      6875990.18
      1432805.00      6875688.00
#Sta/Elev= 30
  3390.6 1938.89  3554.6 1933.85  3644.7 1931.17  3995.0 1922.52  3997.7 1922.52
  4403.4 1917.95  4723.3 1917.23  4783.4 1915.88  4813.4 1916.41  4833.5 1915.32
  4943.7 1913.74  4973.8 1914.90  4983.8 1914.29  4999.4 1911.32  5009.4 1911.31
  5009.7 1910.81  5013.5 1911.31  5032.3 1914.31  5076.0 1915.43  5118.3 1915.87
  5125.7 1916.93  5132.0 1916.45  5168.7 1918.80  5196.3 1917.11  5239.9 1918.57
  5246.2 1918.05  5253.2 1919.01  5325.1 1921.93  5418.5 1924.39  5496.4 1928.00
#Mann=10,-1,0
  3390.6    0.07       0  3554.6   0.035       0  3644.7    0.07       0
  3995.0    0.16       0  3997.7    0.07       0  4403.4   0.035       0
  5009.4   0.035       0  5013.5   0.035       0  5076.0    0.07       0
  5253.2   0.035       0
Bank Sta=5009.4,5013.5
Exp/Cntr=0.3,0.1

Type RM Length L Ch R = 1,6907,498,498,498
BEGIN DESCRIPTION:
Sweetwater Creek Trib 35 4.0
END DESCRIPTION:
XS GIS Cut Line= 3
      1431355.00      6876188.00      1432565.18      6876386.14
      1433154.97      6875738.03
#Sta/Elev= 30
  3773.7 1923.59  3987.7 1920.00  4066.5 1919.17  4521.2 1914.98  4609.5 1914.90
  4614.8 1913.66  4645.2 1915.52  4675.9 1914.03  4734.0 1914.06  4751.1 1913.90
  4949.1 1912.91  4959.3 1912.65  4977.5 1908.40  4987.6 1907.95  4987.9 1907.45
  4991.7 1907.95  5002.1 1908.62  5019.9 1912.41  5034.1 1913.04  5175.3 1912.58
  5388.1 1916.98  5442.3 1919.30  5668.2 1927.85  5678.0 1926.88  5685.5 1927.97
  5706.4 1926.05  5734.8 1930.55  5791.5 1944.68  5840.9 1961.85  5876.3 1968.98
#Mann=10,-1,0
  3773.7   0.035       0  3987.7    0.07       0  4066.5   0.035       0
  4521.2    0.07       0  4734.0   0.035       0  4751.1    0.07       0
  4987.6    0.07       0  4991.7    0.07       0  5442.3   0.035       0
  5668.2    0.07       0
Bank Sta=4987.6,4991.7
Exp/Cntr=0.3,0.1

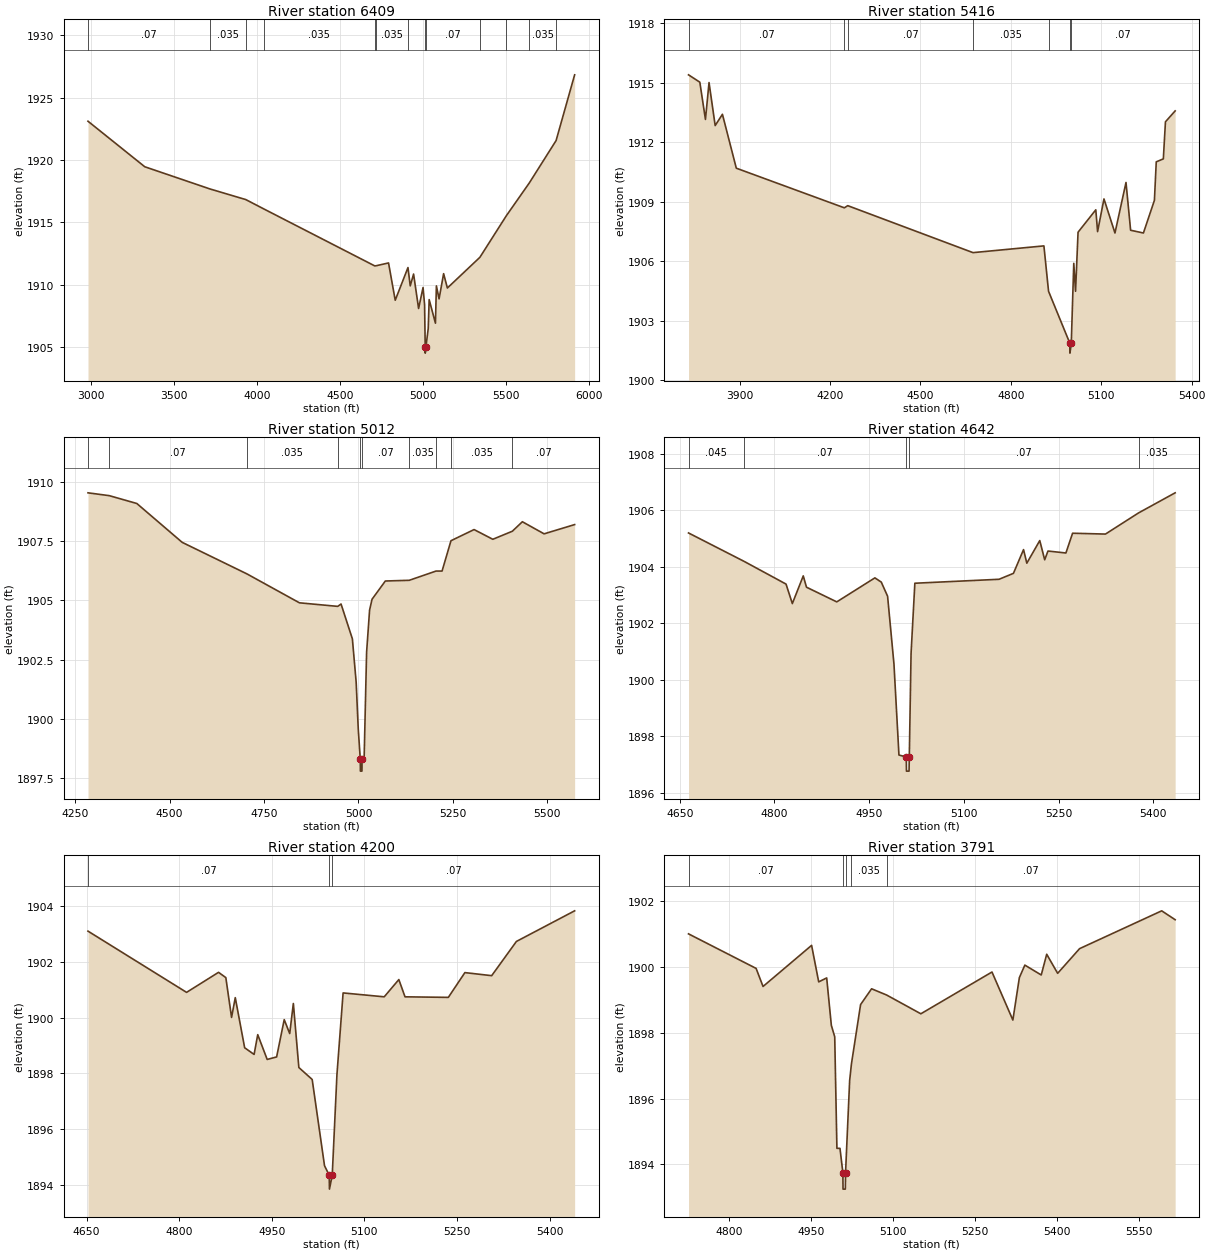
Type RM Length L Ch R = 1,6409,993,993,993
BEGIN DESCRIPTION:
Sweetwater Creek Trib 35 3.0
END DESCRIPTION:
XS GIS Cut Line= 3
      1430804.97      6876988.00      1432813.48      6876784.49
      1433255.01      6875987.98
#Sta/Elev= 30
  2981.2 1923.11  3323.0 1919.46  3715.6 1917.68  3930.9 1916.83  4038.1 1916.09
  4707.8 1911.51  4717.6 1911.53  4790.4 1911.75  4830.7 1908.76  4907.4 1911.38
  4921.1 1909.91  4941.2 1910.86  4971.4 1908.10  4998.2 1909.78  5007.4 1908.40
  5011.2 1905.02  5011.4 1904.52  5015.4 1905.02  5029.3 1906.48  5035.0 1908.81
  5072.8 1906.92  5078.5 1909.91  5094.6 1908.87  5122.0 1910.89  5144.6 1909.74
  5340.3 1912.20  5499.4 1915.53  5637.7 1918.16  5799.1 1921.56  5910.7 1926.83
#Mann=13,-1,0
  2981.2    0.07       0  3715.6   0.035       0  3930.9    0.07       0
  4038.1   0.035       0  4707.8    0.07       0  4717.6   0.035       0
  4907.4    0.07       0  5011.2    0.07       0  5015.4    0.07       0
  5340.3   0.035       0  5499.4    0.07       0  5637.7   0.035       0
  5799.1    0.07       0
Bank Sta=5011.2,5015.4
Exp/Cntr=0.3,0.1

Type RM Length L Ch R = 1,5416,404,404,404
BEGIN DESCRIPTION:
Sweetwater Creek Trib 35 2.0
END DESCRIPTION:
XS GIS Cut Line= 3
      1432428.23      6877184.59      1433673.47      6876937.58
      1433856.52      6876644.80
#Sta/Elev= 30
  3730.5 1915.41  3768.0 1915.04  3786.7 1913.16  3798.6 1915.02  3819.0 1912.85
  3843.0 1913.42  3889.1 1910.70  4247.7 1908.70  4258.8 1908.81  4674.5 1906.44
  4909.8 1906.78  4925.2 1904.49  4995.8 1901.87  4996.2 1901.37  5000.6 1901.87
  5008.9 1905.90  5014.8 1904.49  5023.1 1907.47  5082.0 1908.60  5087.9 1907.50
  5109.1 1909.15  5145.6 1907.43  5182.2 1909.98  5197.5 1907.57  5240.0 1907.43
  5276.5 1909.08  5282.6 1911.02  5306.1 1911.17  5313.1 1913.04  5345.3 1913.59
#Mann=7,-1,0
  3730.5    0.07       0  4247.7   0.045       0  4258.8    0.07       0
  4674.5   0.035       0  4925.2    0.07       0  4995.8    0.07       0
  5000.6    0.07       0
Bank Sta=4995.8,5000.6
Exp/Cntr=0.3,0.1

Type RM Length L Ch R = 1,5012,370,370,370
BEGIN DESCRIPTION:
Sweetwater Creek Trib 35 4421
END DESCRIPTION:
XS GIS Cut Line= 3
      1432915.92      6877242.09      1433631.10      6877214.79
      1434074.69      6876853.66
#Sta/Elev= 30
  4284.3 1909.54  4340.8 1909.42  4413.5 1909.09  4533.6 1907.45  4704.9 1906.12
  4843.8 1904.90  4945.1 1904.75  4953.9 1904.85  4983.9 1903.38  4993.9 1901.55
  4999.4 1899.59  5004.8 1898.30  5005.1 1897.80  5009.2 1897.80  5009.6 1898.30
  5015.1 1898.41  5021.5 1902.81  5029.4 1904.59  5035.9 1905.05  5071.1 1905.82
  5134.4 1905.85  5205.3 1906.24  5221.2 1906.24  5244.8 1907.52  5305.9 1907.99
  5355.5 1907.58  5407.2 1907.92  5433.7 1908.32  5491.2 1907.81  5572.0 1908.20
#Mann=10,-1,0
  4284.3   0.045       0  4340.8    0.07       0  4704.9   0.035       0
  4945.1    0.07       0  5004.8    0.07       0  5009.6    0.07       0
  5134.4   0.035       0  5205.3    0.07       0  5244.8   0.035       0
  5407.2    0.07       0
Bank Sta=5004.8,5009.6
Exp/Cntr=0.3,0.1

Type RM Length L Ch R = 1,4642,442,442,442
BEGIN DESCRIPTION:
Sweetwater Creek Trib 35 4420
END DESCRIPTION:
XS GIS Cut Line= 3
      1433471.45      6877482.98      1433805.66      6877519.55
      1433926.88      6877101.99
#Sta/Elev= 30
  4663.8 1905.19  4752.2 1904.18  4818.3 1903.38  4828.3 1902.69  4845.6 1903.67
  4850.7 1903.27  4898.7 1902.75  4959.1 1903.60  4969.2 1903.45  4979.2 1902.95
  4989.3 1900.55  4997.2 1897.33  5008.8 1897.26  5009.1 1896.76  5013.2 1896.76
  5013.6 1897.26  5016.4 1900.93  5022.4 1903.41  5155.8 1903.55  5178.6 1903.76
  5194.6 1904.60  5199.8 1904.12  5220.3 1904.92  5228.1 1904.24  5233.3 1904.55
  5261.7 1904.48  5272.3 1905.18  5324.4 1905.15  5376.9 1905.90  5434.8 1906.61
#Mann=5,-1,0
  4663.8   0.045       0  4752.2    0.07       0  5008.8    0.07       0
  5013.6    0.07       0  5376.9   0.035       0
Bank Sta=5008.8,5013.6
Exp/Cntr=0.3,0.1

Type RM Length L Ch R = 1,4200,409,409,409
BEGIN DESCRIPTION:
Sweetwater Creek Trib 35 4418
END DESCRIPTION:
XS GIS Cut Line= 3
      1433766.14      6878028.98      1434060.20      6877843.44
      1434026.55      6877404.02
#Sta/Elev= 30
  4652.3 1903.11  4812.0 1900.91  4863.8 1901.63  4875.6 1901.44  4884.9 1900.01
  4890.9 1900.72  4906.1 1898.92  4921.4 1898.68  4927.3 1899.39  4942.6 1898.50
  4957.9 1898.59  4970.2 1899.93  4979.1 1899.43  4985.0 1900.51  4993.9 1898.21
  5015.5 1897.78  5035.5 1894.68  5043.1 1894.34  5043.5 1893.84  5048.0 1894.34
  5055.6 1897.95  5065.6 1900.89  5132.2 1900.75  5155.9 1901.37  5165.9 1900.75
  5236.1 1900.73  5262.9 1901.62  5306.3 1901.51  5346.4 1902.74  5440.7 1903.84
#Mann=3,-1,0
  4652.3    0.07       0  5043.1    0.07       0  5048.0    0.07       0
Bank Sta=5043.1,5048
Exp/Cntr=0.3,0.1

Type RM Length L Ch R = 1,3791,448,448,448
BEGIN DESCRIPTION:
Sweetwater Creek Trib 35 4417
END DESCRIPTION:
XS GIS Cut Line= 4
      1434054.79      6878250.33      1434258.76      6878187.40
      1434294.79      6878138.50      1434323.86      6877523.38
#Sta/Elev= 30
  4725.8 1901.01  4849.4 1899.96  4862.1 1899.41  4950.9 1900.66  4963.9 1899.55
  4978.5 1899.67  4987.0 1898.23  4993.2 1897.88  4997.2 1894.49  5002.8 1894.49
  5008.1 1893.75  5008.4 1893.25  5012.6 1893.25  5013.0 1893.75  5020.5 1896.55
  5023.8 1897.06  5040.5 1898.86  5060.6 1899.34  5088.2 1899.15  5150.7 1898.58
  5280.8 1899.85  5319.0 1898.39  5330.9 1899.68  5340.9 1900.06  5370.9 1899.76
  5380.9 1900.39  5400.9 1899.81  5441.0 1900.56  5591.2 1901.71  5615.8 1901.44
#Mann=5,-1,0
  4725.8    0.07       0  5008.1    0.07       0  5013.0    0.07       0
  5023.8   0.035       0  5088.2    0.07       0
Bank Sta=5008.1,5013
Exp/Cntr=0.3,0.1

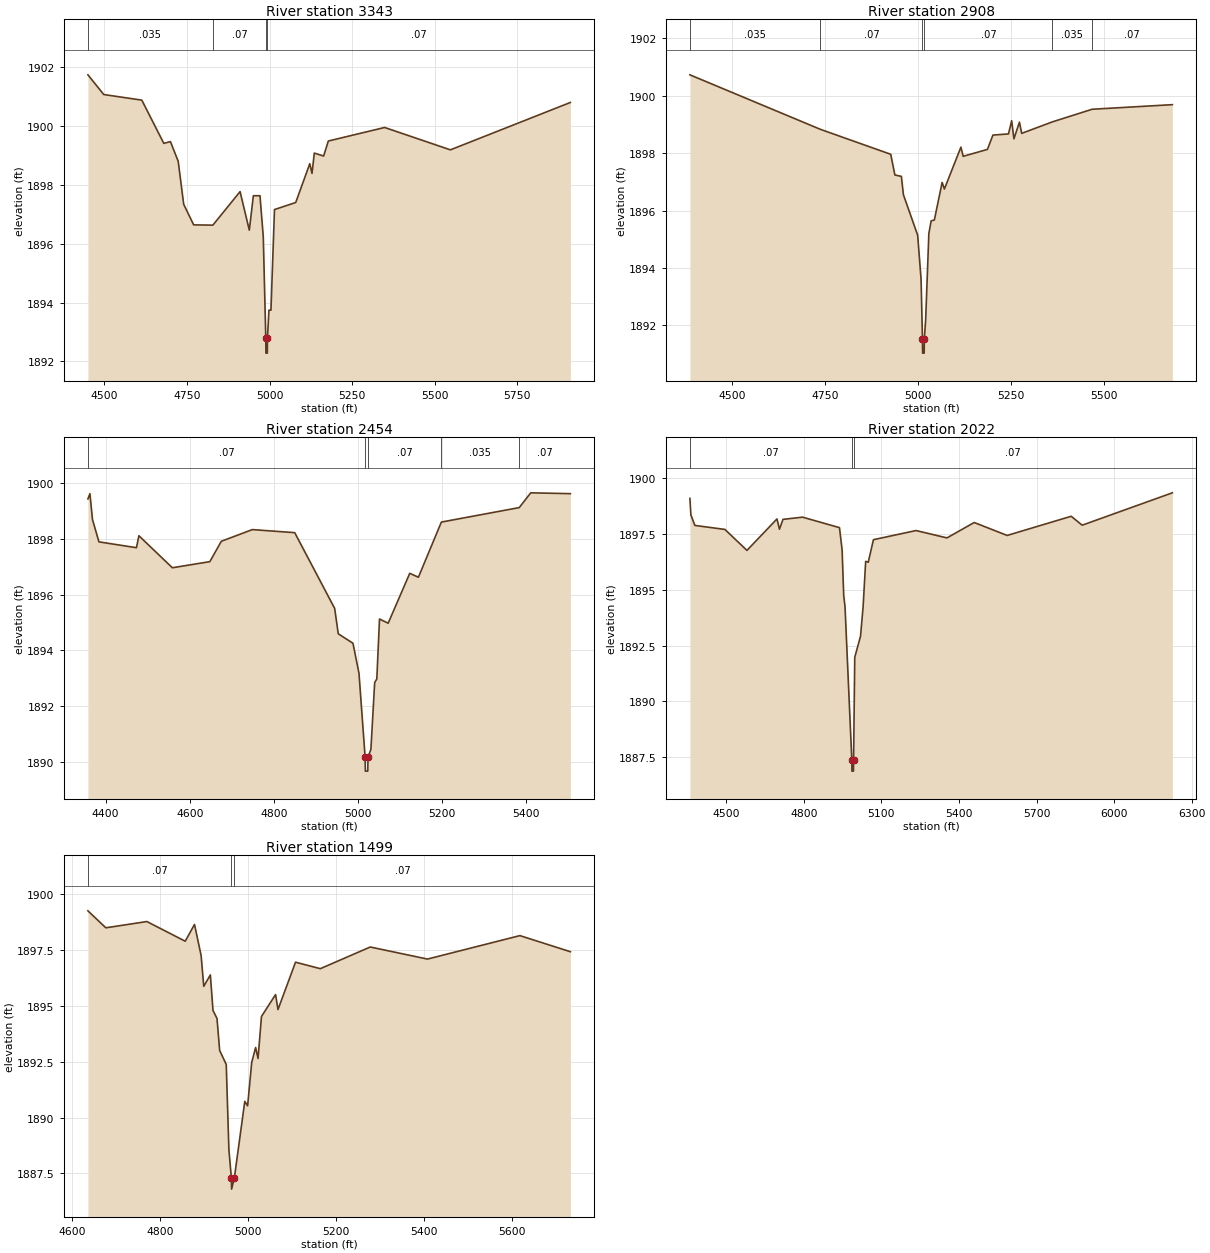
Type RM Length L Ch R = 1,3343,435,435,435
BEGIN DESCRIPTION:
Sweetwater Creek Trib 35 4416
END DESCRIPTION:
XS GIS Cut Line= 4
      1433946.18      6878328.26      1434494.09      6878378.33
      1434706.35      6878188.66      1434893.48      6877591.45
#Sta/Elev= 30
  4449.8 1901.74  4497.8 1901.07  4613.0 1900.88  4679.6 1899.41  4699.7 1899.47
  4723.2 1898.80  4739.8 1897.34  4770.0 1896.64  4828.1 1896.63  4910.5 1897.77
  4938.5 1896.46  4950.7 1897.63  4970.8 1897.63  4980.8 1896.23  4988.4 1892.78
  4988.8 1892.28  4993.0 1892.28  4993.4 1892.78  4997.9 1893.74  5004.0 1893.74
  5014.7 1897.16  5079.0 1897.40  5121.6 1898.72  5128.3 1898.39  5135.3 1899.08
  5163.5 1898.98  5177.7 1899.49  5348.2 1899.95  5547.3 1899.19  5910.5 1900.80
#Mann=4,-1,0
  4449.8   0.035       0  4828.1    0.07       0  4988.4    0.07       0
  4993.4    0.07       0
Bank Sta=4988.4,4993.4
Exp/Cntr=0.3,0.1

Type RM Length L Ch R = 1,2908,454,454,454
BEGIN DESCRIPTION:
Sweetwater Creek Trib 35 4415
END DESCRIPTION:
XS GIS Cut Line= 5
      1434086.84      6878522.30      1434356.35      6878845.19
      1434531.58      6878764.76      1434753.55      6878452.16
      1434789.95      6878153.76
#Sta/Elev= 30
  4386.6 1900.73  4737.5 1898.83  4926.7 1897.96  4937.8 1897.24  4955.3 1897.19
  4960.8 1896.55  4999.1 1895.14  5008.3 1893.60  5012.0 1891.53  5012.4 1891.03
  5016.6 1891.03  5017.0 1891.53  5020.6 1892.19  5029.2 1895.20  5035.4 1895.64
  5044.0 1895.67  5064.9 1896.98  5071.0 1896.75  5115.4 1898.21  5121.5 1897.89
  5186.7 1898.13  5201.5 1898.63  5243.3 1898.67  5251.9 1899.13  5258.0 1898.50
  5272.8 1899.08  5278.9 1898.69  5361.4 1899.09  5468.3 1899.53  5684.0 1899.69
#Mann=6,-1,0
  4386.6   0.035       0  4737.5    0.07       0  5012.0    0.07       0
  5017.0    0.07       0  5361.4   0.035       0  5468.3    0.07       0
Bank Sta=5012,5017
Exp/Cntr=0.3,0.1

Type RM Length L Ch R = 1,2454,432,432,432
BEGIN DESCRIPTION:
Sweetwater Creek Trib 35 1.0
END DESCRIPTION:
XS GIS Cut Line= 3
      1434587.61      6879287.32      1434919.99      6878737.94
      1434804.28      6878246.27
#Sta/Elev= 30
  4357.9 1899.43  4362.7 1899.62  4368.8 1898.69  4384.1 1897.89  4473.3 1897.68
  4479.1 1898.11  4558.7 1896.96  4647.9 1897.18  4675.1 1897.91  4748.8 1898.33
  4849.7 1898.22  4944.7 1895.50  4953.2 1894.59  4988.2 1894.25  5002.5 1893.17
  5017.1 1890.16  5017.6 1889.66  5023.4 1889.66  5023.9 1890.16  5030.8 1890.44
  5039.8 1892.84  5044.9 1892.97  5051.3 1895.12  5071.9 1894.97  5123.2 1896.76
  5143.8 1896.62  5198.4 1898.60  5383.6 1899.12  5410.9 1899.65  5505.1 1899.62
#Mann=5,-1,0
  4357.9    0.07       0  5017.1    0.07       0  5023.9    0.07       0
  5198.4   0.035       0  5383.6    0.07       0
Bank Sta=5017.1,5023.9
Exp/Cntr=0.3,0.1

Type RM Length L Ch R = 1,2022,523,523,523
BEGIN DESCRIPTION:
Sweetwater Creek Trib 35 4413
END DESCRIPTION:
XS GIS Cut Line= 6
      1434607.39      6879285.18      1434811.06      6878951.73
      1435055.82      6879001.98      1435290.06      6879000.13
      1435444.64      6878812.51      1434934.98      6878265.07
#Sta/Elev= 30
  4359.4 1899.10  4363.2 1898.36  4378.6 1897.89  4494.8 1897.71  4580.0 1896.77
  4696.2 1898.18  4705.8 1897.72  4719.3 1898.16  4795.0 1898.26  4937.9 1897.79
  4948.1 1896.79  4954.3 1894.75  4959.4 1894.24  4985.6 1887.38  4986.1 1886.88
  4991.9 1886.88  4992.4 1887.38  4997.0 1891.98  5019.2 1892.92  5029.2 1894.23
  5039.2 1896.28  5049.2 1896.24  5069.2 1897.25  5234.2 1897.66  5353.6 1897.33
  5459.0 1898.02  5586.4 1897.44  5834.1 1898.30  5876.6 1897.90  6225.3 1899.35
#Mann=3,-1,0
  4359.4    0.07       0  4985.6    0.07       0  4992.4    0.07       0
Bank Sta=4985.6,4992.4
Exp/Cntr=0.3,0.1

Type RM Length L Ch R = 1,1499,0,0,0
BEGIN DESCRIPTION:
Sweetwater Creek Trib 35 27
END DESCRIPTION:
XS GIS Cut Line= 3
      1434908.53      6879537.16      1435210.97      6879335.86
      1435527.51      6878675.40
#Sta/Elev= 30
  4636.7 1899.26  4677.4 1898.50  4770.6 1898.78  4857.7 1897.90  4878.8 1898.65
  4893.8 1897.26  4899.8 1895.88  4914.8 1896.39  4920.8 1894.80  4929.9 1894.44
  4935.9 1893.01  4950.9 1892.38  4956.9 1888.57  4962.5 1887.30  4963.0 1886.80
  4969.3 1887.30  4993.0 1890.73  4999.4 1890.53  5008.7 1892.47  5017.6 1893.14
  5023.1 1892.65  5030.9 1894.53  5062.9 1895.51  5068.4 1894.84  5108.2 1896.96
  5164.6 1896.67  5277.9 1897.64  5407.9 1897.10  5617.8 1898.15  5732.4 1897.43
#Mann=3,-1,0
  4636.7    0.07       0  4962.5    0.07       0  4969.3    0.07       0
Bank Sta=4962.5,4969.3
Exp/Cntr=0.3,0.1

Chan Stop Cuts=-1