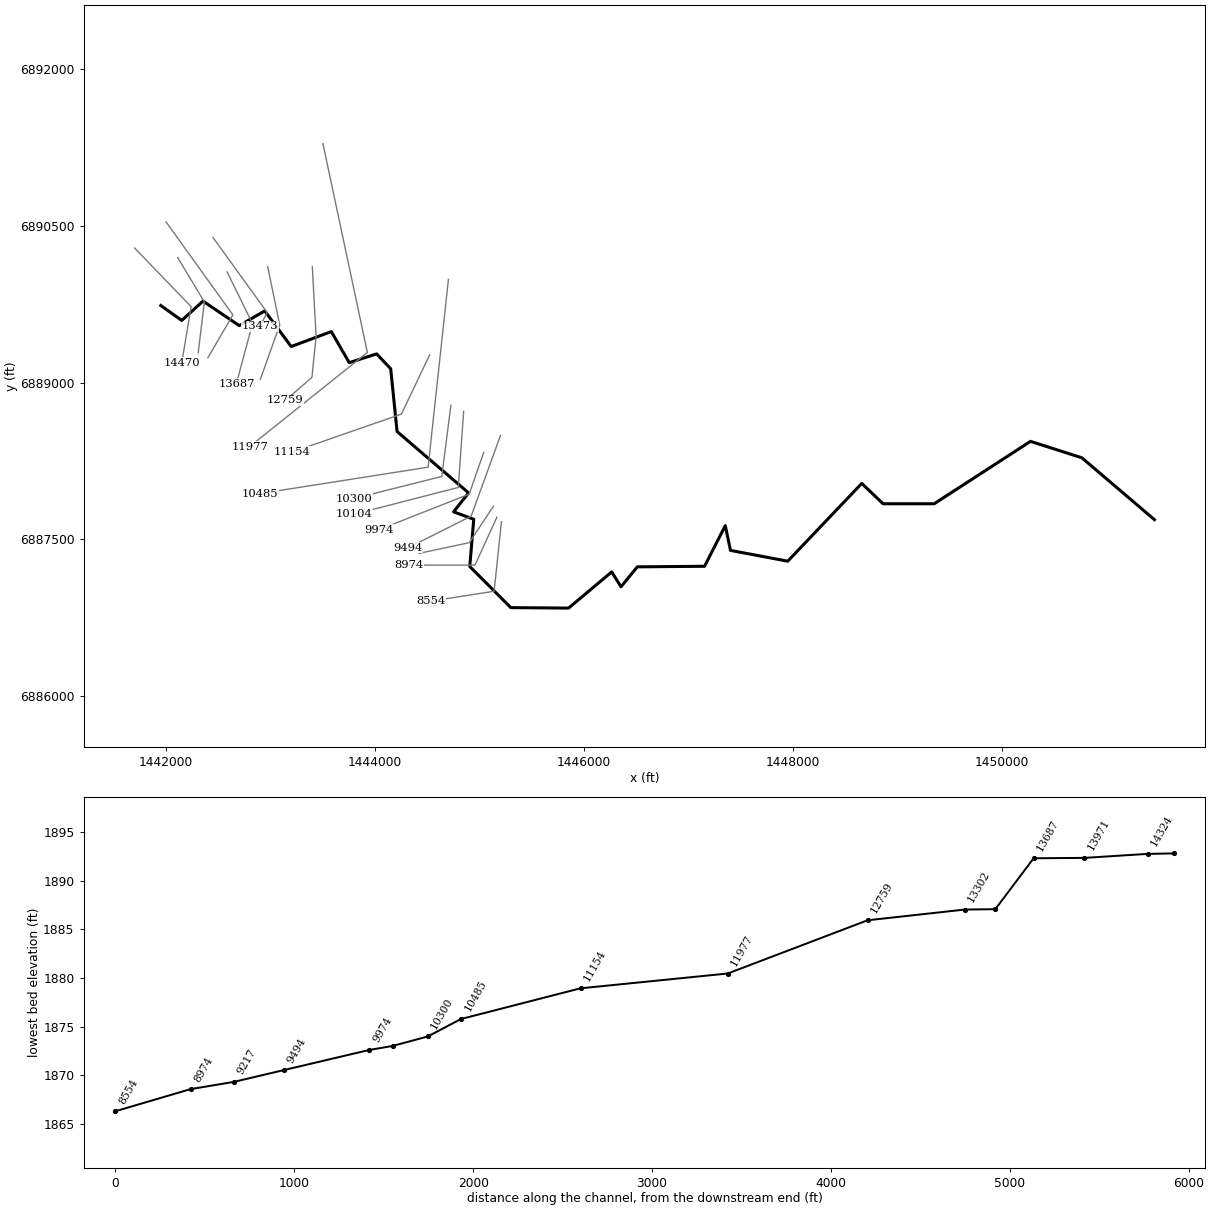
--- Sweetwater Creek Trib 36.prj (project) ---

Proj Title=Sweetwater Creek Trib 36 Base Level Engineering
Current Plan=p01
Default Exp/Contr=0.3,0.1
English Units
Geom File=g01
Flow File=f01
Plan File=p01
BEGIN DESCRIPTION:
Sweetwater Creek Trib 36
END DESCRIPTION:

--- Sweetwater Creek Trib 36.p01 (plan) ---

Plan Title=Multiple Run
Short Identifier=Multiple
Geom File=g01
Flow File=f01
Subcritical Flow
K Sum by GR= 0
Std Step Tol= 0.01
Critical Tol= 0.01
Num of Std Step Trials= 20
Max Error Tol= 0.3
Flow Tol Ratio= 0.001
Split Flow NTrial= 30
Split Flow Tol= 0.02
Split Flow Ratio= 0.02
Log Output Level= 0
Friction Slope Method= 1
Unsteady Friction Slope Method= 2
Unsteady Bridges Friction Slope Method= 1
Parabolic Critical Depth
Global Vel Dist=  1 , 1 , 1
Global Log Level= 0
CheckData=True
Encroach Param= -1, 0, 0, 0
BEGIN DESCRIPTION:
Multiple Run
END DESCRIPTION:

--- Sweetwater Creek Trib 36.f01 (steady flow) ---

Flow Title=Multiple
Number of Profiles=7
Profile Names=10-year,25-year,50-year,1pct_min,100-year,1pct_plu,500-year
River Rch & RM= Sweetwater Creek,Reach-1,14470
     212     291     355     215     429     857     637
River Rch & RM= Sweetwater Creek,Reach-1,13302
     355     502     624     385     769    1535    1184
Boundary for River Rch & Prof#=Sweetwater Creek,Reach-1,1
Up Type=0
Dn Type=3
Dn Slope=0.005
Boundary for River Rch & Prof#=Sweetwater Creek,Reach-1,2
Up Type=0
Dn Type=3
Dn Slope=0.005
Boundary for River Rch & Prof#=Sweetwater Creek,Reach-1,3
Up Type=0
Dn Type=3
Dn Slope=0.005
Boundary for River Rch & Prof#=Sweetwater Creek,Reach-1,4
Up Type=0
Dn Type=3
Dn Slope=0.005
Boundary for River Rch & Prof#=Sweetwater Creek,Reach-1,5
Up Type=0
Dn Type=3
Dn Slope=0.005
Boundary for River Rch & Prof#=Sweetwater Creek,Reach-1,6
Up Type=0
Dn Type=3
Dn Slope=0.005
Boundary for River Rch & Prof#=Sweetwater Creek,Reach-1,7
Up Type=0
Dn Type=3
Dn Slope=0.005

--- Sweetwater Creek Trib 36.g01 (geometry) ---

Geom Title=Existing Conditions

River Reach=Sweetwater Creek,Reach-1
Reach XY= 30
      1441955.00      6889738.00      1442155.21      6889594.98
      1442358.41      6889780.23      1442704.79      6889545.45
      1442948.57      6889686.58      1443201.56      6889345.42
      1443585.08      6889488.25      1443756.65      6889191.10
      1444018.63      6889274.74      1444153.01      6889132.32
      1444214.13      6888531.26      1444897.66      6887944.31
      1444754.37      6887762.90      1444947.31      6887691.74
      1444908.82      6887239.59      1445301.33      6886845.69
      1445853.37      6886841.13      1446266.19      6887187.50
      1446354.77      6887044.97      1446510.71      6887236.11
      1447153.75      6887241.45      1447351.86      6887630.50
      1447401.99      6887393.46      1447949.09      6887290.22
      1448656.74      6888034.69      1448860.78      6887839.89
      1449349.15      6887840.06      1450270.22      6888437.50
      1450761.17      6888280.14      1451455.00      6887688.00

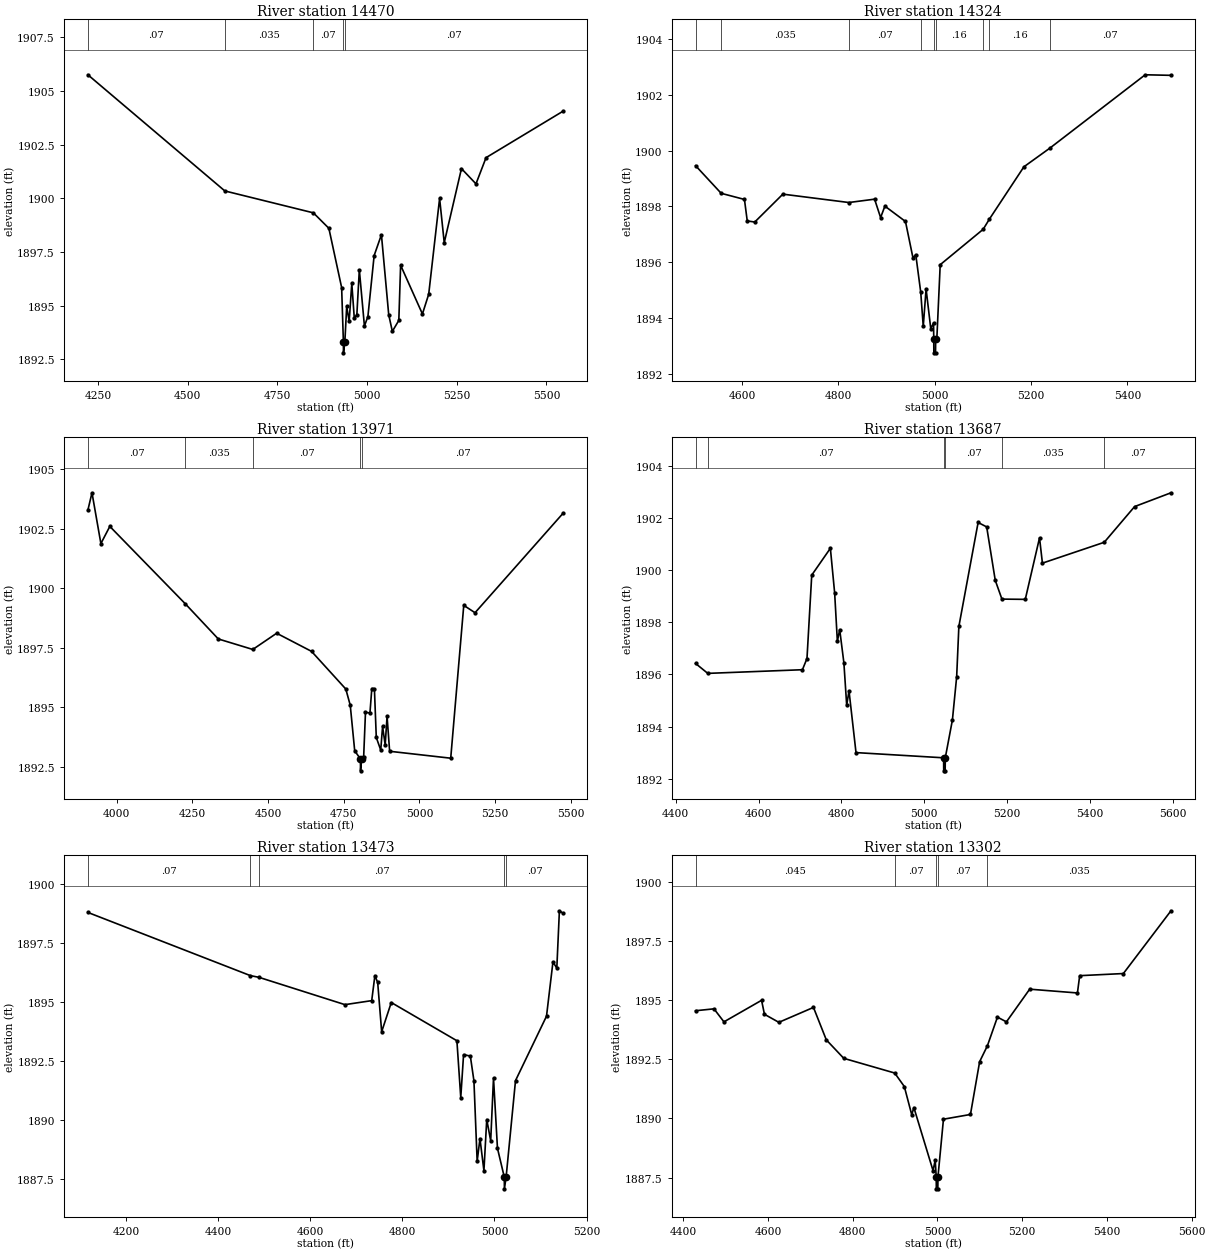
Type RM Length L Ch R = 1,14470,146,146,146
BEGIN DESCRIPTION:
Sweetwater Creek Trib 36 14.0
END DESCRIPTION:
XS GIS Cut Line= 3
      1441705.00      6890288.00      1442245.00      6889727.38
      1442155.01      6889188.04
#Sta/Elev= 30
  4221.6 1905.75  4603.4 1900.34  4850.2 1899.32  4893.4 1898.60  4929.0 1895.84
  4933.9 1893.30  4934.1 1892.80  4937.9 1893.30  4943.1 1894.96  4950.0 1894.27
  4957.3 1896.03  4964.2 1894.43  4971.4 1894.57  4978.3 1896.67  4992.5 1894.05
  5002.2 1894.49  5019.6 1897.33  5039.9 1898.30  5060.2 1894.58  5070.3 1893.80
  5088.4 1894.31  5093.4 1896.88  5154.2 1894.61  5171.7 1895.53  5202.1 1899.99
  5215.0 1897.93  5263.0 1901.38  5303.5 1900.67  5331.5 1901.89  5546.8 1904.06
#Mann=5,-1,0
  4221.6    0.07       0  4603.4   0.035       0  4850.2    0.07       0
  4933.9    0.07       0  4937.9    0.07       0
Bank Sta=4933.9,4937.9
Exp/Cntr=0.3,0.1

Type RM Length L Ch R = 1,14324,353,353,353
BEGIN DESCRIPTION:
Sweetwater Creek Trib 36 4097
END DESCRIPTION:
XS GIS Cut Line= 3
      1442116.14      6890197.16      1442371.70      6889771.72
      1442312.46      6889284.91
#Sta/Elev= 30
  4503.7 1899.46  4556.8 1898.47  4605.1 1898.25  4610.9 1897.48  4626.5 1897.44
  4684.8 1898.44  4821.8 1898.14  4875.2 1898.26  4887.7 1897.60  4896.6 1898.01
  4939.3 1897.46  4954.8 1896.16  4960.7 1896.27  4971.0 1894.92  4976.2 1893.70
  4982.1 1895.04  4991.8 1893.62  4997.6 1893.82  4998.0 1893.25  4998.2 1892.75
  5001.7 1892.75  5002.0 1893.25  5004.4 1893.25  5011.4 1895.91  5100.6 1897.18
  5113.7 1897.55  5185.1 1899.42  5239.0 1900.09  5436.9 1902.72  5490.4 1902.70
#Mann=9,-1,0
  4503.7    0.07       0  4556.8   0.035       0  4821.8    0.07       0
  4971.0    0.16       0  4998.0    0.07       0  5002.0    0.16       0
  5100.6    0.07       0  5113.7    0.16       0  5239.0    0.07       0
Bank Sta=4998,5002
Exp/Cntr=0.3,0.1

Type RM Length L Ch R = 1,13971,284,284,284
BEGIN DESCRIPTION:
Sweetwater Creek Trib 36 13.0
END DESCRIPTION:
XS GIS Cut Line= 3
      1442004.98      6890538.03      1442644.23      6889648.37
      1442405.01      6889238.01
#Sta/Elev= 30
  3904.5 1903.27  3918.1 1904.00  3947.5 1901.87  3977.0 1902.59  4226.7 1899.34
  4335.4 1897.87  4449.3 1897.43  4528.2 1898.11  4643.4 1897.35  4756.6 1895.77
  4771.3 1895.09  4786.0 1893.18  4804.9 1892.84  4805.2 1892.34  4808.9 1892.84
  4815.5 1892.90  4821.6 1894.79  4836.4 1894.77  4842.5 1895.79  4851.1 1895.78
  4857.3 1893.74  4872.0 1893.21  4878.1 1894.20  4886.7 1893.43  4892.9 1894.62
  4901.4 1893.16  5103.2 1892.87  5146.3 1899.28  5183.5 1898.97  5475.0 1903.15
#Mann=5,-1,0
  3904.5    0.07       0  4226.7   0.035       0  4449.3    0.07       0
  4804.9    0.07       0  4808.9    0.07       0
Bank Sta=4804.9,4808.9
Exp/Cntr=0.3,0.1

Type RM Length L Ch R = 1,13687,214,214,214
BEGIN DESCRIPTION:
Sweetwater Creek Trib 36 4096
END DESCRIPTION:
XS GIS Cut Line= 3
      1442589.01      6890059.64      1442831.72      6889563.75
      1442677.19      6888988.14
#Sta/Elev= 30
  4447.9 1896.42  4477.3 1896.04  4705.9 1896.18  4716.9 1896.61  4728.4 1899.81
  4773.4 1900.84  4783.7 1899.13  4790.3 1897.27  4795.9 1897.72  4806.0 1896.45
  4812.8 1894.82  4818.4 1895.37  4835.3 1893.00  5046.9 1892.80  5047.1 1892.30
  5050.6 1892.30  5050.9 1892.80  5068.1 1894.25  5078.4 1895.91  5083.7 1897.84
  5130.2 1901.83  5150.9 1901.66  5171.6 1899.61  5187.7 1898.89  5244.1 1898.88
  5278.5 1901.24  5285.5 1900.27  5434.8 1901.07  5508.1 1902.44  5596.0 1902.97
#Mann=6,-1,0
  4447.9   0.035       0  4477.3    0.07       0  5046.9    0.07       0
  5050.9    0.07       0  5187.7   0.035       0  5434.8    0.07       0
Bank Sta=5046.9,5050.9
Exp/Cntr=0.3,0.1

Type RM Length L Ch R = 1,13473,171,171,171
BEGIN DESCRIPTION:
Sweetwater Creek Trib 36 12.0
END DESCRIPTION:
XS GIS Cut Line= 3
      1442455.03      6890387.97      1442971.48      6889671.87
      1442904.99      6889537.97
#Sta/Elev= 30
  4117.1 1898.79  4470.1 1896.11  4488.4 1896.04  4675.4 1894.88  4733.5 1895.05
  4740.4 1896.11  4746.5 1895.82  4755.1 1893.73  4776.0 1894.97  4918.5 1893.35
  4926.9 1890.94  4933.0 1892.76  4947.7 1892.70  4955.5 1891.65  4962.5 1888.24
  4968.6 1889.20  4977.2 1887.84  4983.3 1890.01  4991.9 1889.11  4998.0 1891.77
  5006.6 1888.79  5021.4 1887.57  5021.7 1887.07  5025.4 1887.57  5045.8 1891.66
  5113.1 1894.39  5127.1 1896.69  5135.5 1896.43  5141.1 1898.86  5149.5 1898.75
#Mann=5,-1,0
  4117.1    0.07       0  4470.1   0.035       0  4488.4    0.07       0
  5021.4    0.07       0  5025.4    0.07       0
Bank Sta=5021.4,5025.4
Exp/Cntr=0.3,0.1

Type RM Length L Ch R = 1,13302,543,543,543
BEGIN DESCRIPTION:
Sweetwater Creek Trib 36 4095
END DESCRIPTION:
XS GIS Cut Line= 3
      1442976.96      6890110.51      1443091.79      6889551.38
      1442906.99      6889032.09
#Sta/Elev= 30
  4429.2 1894.55  4472.6 1894.63  4496.1 1894.08  4584.9 1894.99  4591.7 1894.40
  4625.7 1894.06  4707.4 1894.69  4737.7 1893.32  4778.9 1892.54  4899.1 1891.92
  4921.8 1891.35  4939.3 1890.16  4944.4 1890.46  4989.6 1887.80  4994.7 1888.24
  4997.1 1887.53  4997.4 1887.03  5000.9 1887.03  5001.2 1887.53  5014.2 1889.97
  5077.9 1890.17  5099.6 1892.40  5117.9 1893.07  5141.6 1894.28  5162.8 1894.08
  5217.7 1895.46  5330.4 1895.30  5335.7 1896.03  5438.8 1896.12  5551.2 1898.77
#Mann=5,-1,0
  4429.2   0.045       0  4899.1    0.07       0  4997.1    0.07       0
  5001.2    0.07       0  5117.9   0.035       0
Bank Sta=4997.1,5001.2
Exp/Cntr=0.3,0.1

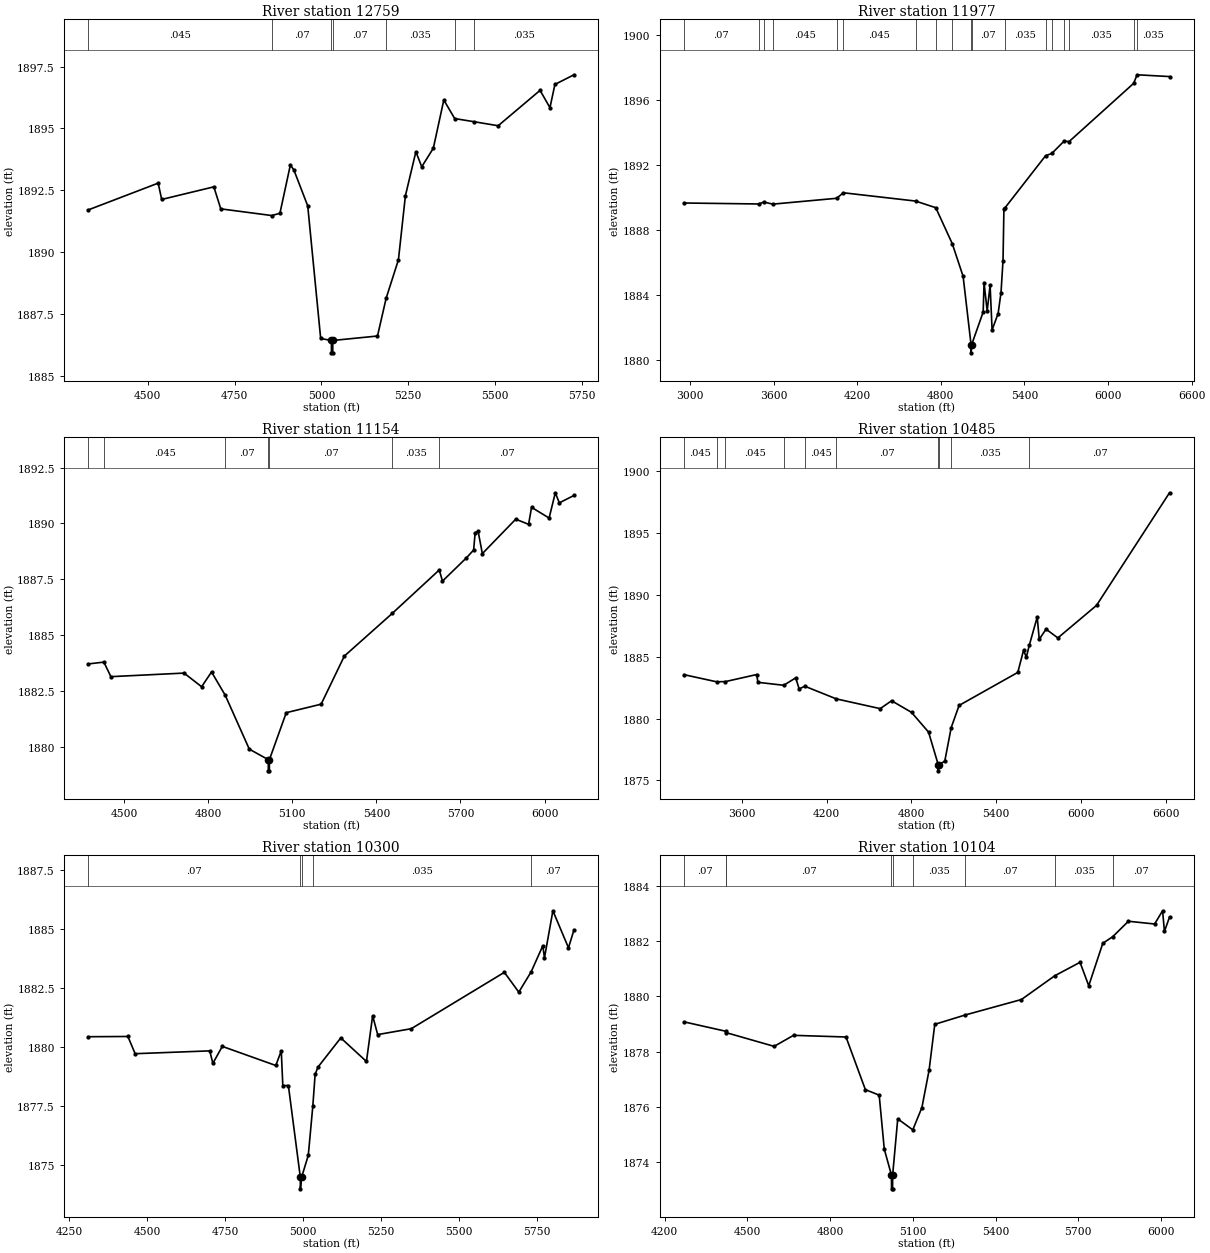
Type RM Length L Ch R = 1,12759,782,782,782
BEGIN DESCRIPTION:
Sweetwater Creek Trib 36 4094
END DESCRIPTION:
XS GIS Cut Line= 4
      1443403.66      6890108.75      1443439.78      6889438.53
      1443399.67      6889049.11      1443145.31      6888829.84
#Sta/Elev= 30
  4328.8 1891.71  4529.8 1892.79  4539.9 1892.13  4690.1 1892.64  4710.1 1891.75
  4856.9 1891.48  4880.4 1891.57  4910.4 1893.52  4920.4 1893.33  4960.5 1891.87
  4997.8 1886.51  5028.6 1886.43  5028.9 1885.93  5032.5 1885.93  5032.7 1886.43
  5161.4 1886.61  5186.4 1888.14  5221.7 1889.69  5241.8 1892.28  5272.0 1894.06
  5288.8 1893.45  5322.2 1894.20  5352.4 1896.15  5383.8 1895.40  5440.6 1895.27
  5509.0 1895.11  5629.6 1896.54  5658.1 1895.84  5672.4 1896.78  5727.3 1897.17
#Mann=7,-1,0
  4328.8   0.045       0  4856.9    0.07       0  5028.6    0.07       0
  5032.7    0.07       0  5186.4   0.035       0  5383.8    0.07       0
  5440.6   0.035       0
Bank Sta=5028.6,5032.7
Exp/Cntr=0.3,0.1

Type RM Length L Ch R = 1,11977,823,823,823
BEGIN DESCRIPTION:
Sweetwater Creek Trib 36 11.0
END DESCRIPTION:
XS GIS Cut Line= 3
      1443504.99      6891288.04      1443929.98      6889288.51
      1442805.00      6888388.00
#Sta/Elev= 30
  2955.8 1889.68  3493.7 1889.62  3529.2 1889.74  3593.9 1889.61  4052.2 1889.97
  4099.9 1890.31  4618.2 1889.80  4763.5 1889.39  4881.6 1887.18  4959.6 1885.17
  5016.7 1880.96  5017.0 1880.46  5020.8 1880.96  5103.6 1882.97  5110.0 1884.77
  5132.4 1883.04  5153.3 1884.62  5167.7 1881.87  5210.9 1882.88  5231.7 1884.17
  5246.1 1886.14  5252.5 1889.32  5261.8 1889.40  5551.6 1892.59  5596.4 1892.73
  5684.5 1893.49  5720.4 1893.46  6183.3 1897.04  6208.4 1897.57  6441.0 1897.46
#Mann=18,-1,0
  2955.8    0.07       0  3493.7   0.045       0  3529.2    0.07       0
  3593.9   0.045       0  4052.2    0.07       0  4099.9   0.045       0
  4618.2   0.035       0  4763.5   0.045       0  4881.6    0.07       0
  5016.7    0.07       0  5020.8    0.07       0  5261.8   0.035       0
  5551.6    0.16       0  5596.4   0.035       0  5684.5    0.16       0
  5720.4   0.035       0  6183.3    0.07       0  6208.4   0.035       0
Bank Sta=5016.7,5020.8
Exp/Cntr=0.3,0.1

Type RM Length L Ch R = 1,11154,669,669,669
BEGIN DESCRIPTION:
Sweetwater Creek Trib 36 4093
END DESCRIPTION:
XS GIS Cut Line= 3
      1444524.98      6889264.60      1444255.60      6888698.52
      1443212.11      6888335.30
#Sta/Elev= 30
  4373.1 1883.72  4428.3 1883.80  4453.4 1883.15  4714.3 1883.31  4776.9 1882.70
  4812.3 1883.36  4861.1 1882.32  4947.0 1879.91  5014.6 1879.44  5014.9 1878.94
  5018.5 1878.94  5018.7 1879.44  5078.8 1881.54  5203.2 1881.92  5285.9 1884.07
  5457.0 1885.98  5624.5 1887.92  5635.9 1887.42  5721.2 1888.46  5747.0 1888.81
  5752.4 1889.58  5763.0 1889.65  5778.1 1888.65  5897.2 1890.19  5943.0 1889.96
  5953.6 1890.72  6016.2 1890.24  6038.3 1891.37  6052.6 1890.92  6104.9 1891.25
#Mann=7,-1,0
  4373.1   0.035       0  4428.3   0.045       0  4861.1    0.07       0
  5014.6    0.07       0  5018.7    0.07       0  5457.0   0.035       0
  5624.5    0.07       0
Bank Sta=5014.6,5018.7
Exp/Cntr=0.3,0.1

Type RM Length L Ch R = 1,10485,185,185,185
BEGIN DESCRIPTION:
Sweetwater Creek Trib 36 22
END DESCRIPTION:
XS GIS Cut Line= 3
      1444705.00      6889988.04      1444510.78      6888190.10
      1442905.04      6887938.01
#Sta/Elev= 30
  3191.6 1883.56  3423.7 1882.98  3485.5 1883.00  3706.7 1883.57  3714.7 1882.94
  3897.4 1882.70  3982.1 1883.30  4006.4 1882.41  4047.2 1882.62  4269.2 1881.60
  4579.7 1880.81  4660.1 1881.45  4801.0 1880.51  4921.7 1878.91  4989.9 1876.28
  4990.2 1875.78  4994.2 1876.28  5036.2 1876.56  5081.5 1879.27  5137.4 1881.07
  5552.5 1883.74  5593.0 1885.52  5613.2 1884.98  5634.7 1885.97  5689.8 1888.21
  5704.3 1886.42  5752.4 1887.24  5835.9 1886.53  6109.2 1889.16  6625.4 1898.27
#Mann=10,-1,0
  3191.6   0.045       0  3423.7    0.07       0  3485.5   0.045       0
  3897.4   0.035       0  4047.2   0.045       0  4269.2    0.07       0
  4989.9    0.07       0  4994.2    0.07       0  5081.5   0.035       0
  5634.7    0.07       0
Bank Sta=4989.9,4994.2
Exp/Cntr=0.3,0.1

Type RM Length L Ch R = 1,10300,196,196,196
BEGIN DESCRIPTION:
Sweetwater Creek Trib 36 4092
END DESCRIPTION:
XS GIS Cut Line= 3
      1444728.74      6888783.60      1444641.47      6888101.56
      1443799.44      6887889.60
#Sta/Elev= 30
  4312.4 1880.44  4439.0 1880.45  4462.2 1879.72  4701.3 1879.84  4711.2 1879.31
  4741.5 1880.03  4912.9 1879.22  4930.4 1879.84  4935.4 1878.37  4953.2 1878.37
  4991.4 1874.49  4991.7 1873.99  4995.7 1874.49  5017.0 1875.41  5031.5 1877.50
  5038.9 1878.84  5047.9 1879.15  5121.1 1880.39  5203.3 1879.39  5223.2 1881.33
  5239.3 1880.53  5347.0 1880.78  5645.2 1883.17  5691.5 1882.33  5731.0 1883.19
  5768.5 1884.30  5773.7 1883.78  5800.7 1885.78  5850.7 1884.21  5868.3 1884.97
#Mann=5,-1,0
  4312.4    0.07       0  4991.4    0.07       0  4995.7    0.07       0
  5031.5   0.035       0  5731.0    0.07       0
Bank Sta=4991.4,4995.7
Exp/Cntr=0.3,0.1

Type RM Length L Ch R = 1,10104,130,130,130
BEGIN DESCRIPTION:
Sweetwater Creek Trib 36 4086
END DESCRIPTION:
XS GIS Cut Line= 3
      1444850.60      6888724.36      1444798.98      6887996.18
      1443800.74      6887738.76
#Sta/Elev= 30
  4270.0 1879.08  4421.0 1878.74  4422.6 1878.69  4597.2 1878.19  4667.4 1878.59
  4857.8 1878.53  4928.0 1876.62  4978.1 1876.42  4996.6 1874.46  5022.6 1873.52
  5022.9 1873.02  5026.7 1873.02  5026.9 1873.52  5045.4 1875.56  5100.0 1875.16
  5133.0 1875.97  5159.0 1877.32  5179.7 1878.99  5290.6 1879.33  5494.0 1879.89
  5614.5 1880.75  5706.4 1881.24  5738.0 1880.39  5789.0 1881.93  5825.0 1882.17
  5881.9 1882.73  5976.9 1882.63  6005.8 1883.11  6012.5 1882.36  6030.9 1882.88
#Mann=9,-1,0
  4270.0    0.07       0  4421.0   0.035       0  4422.6    0.07       0
  5022.6    0.07       0  5026.9    0.07       0  5100.0   0.035       0
  5290.6    0.07       0  5614.5   0.035       0  5825.0    0.07       0
Bank Sta=5022.6,5026.9
Exp/Cntr=0.3,0.1

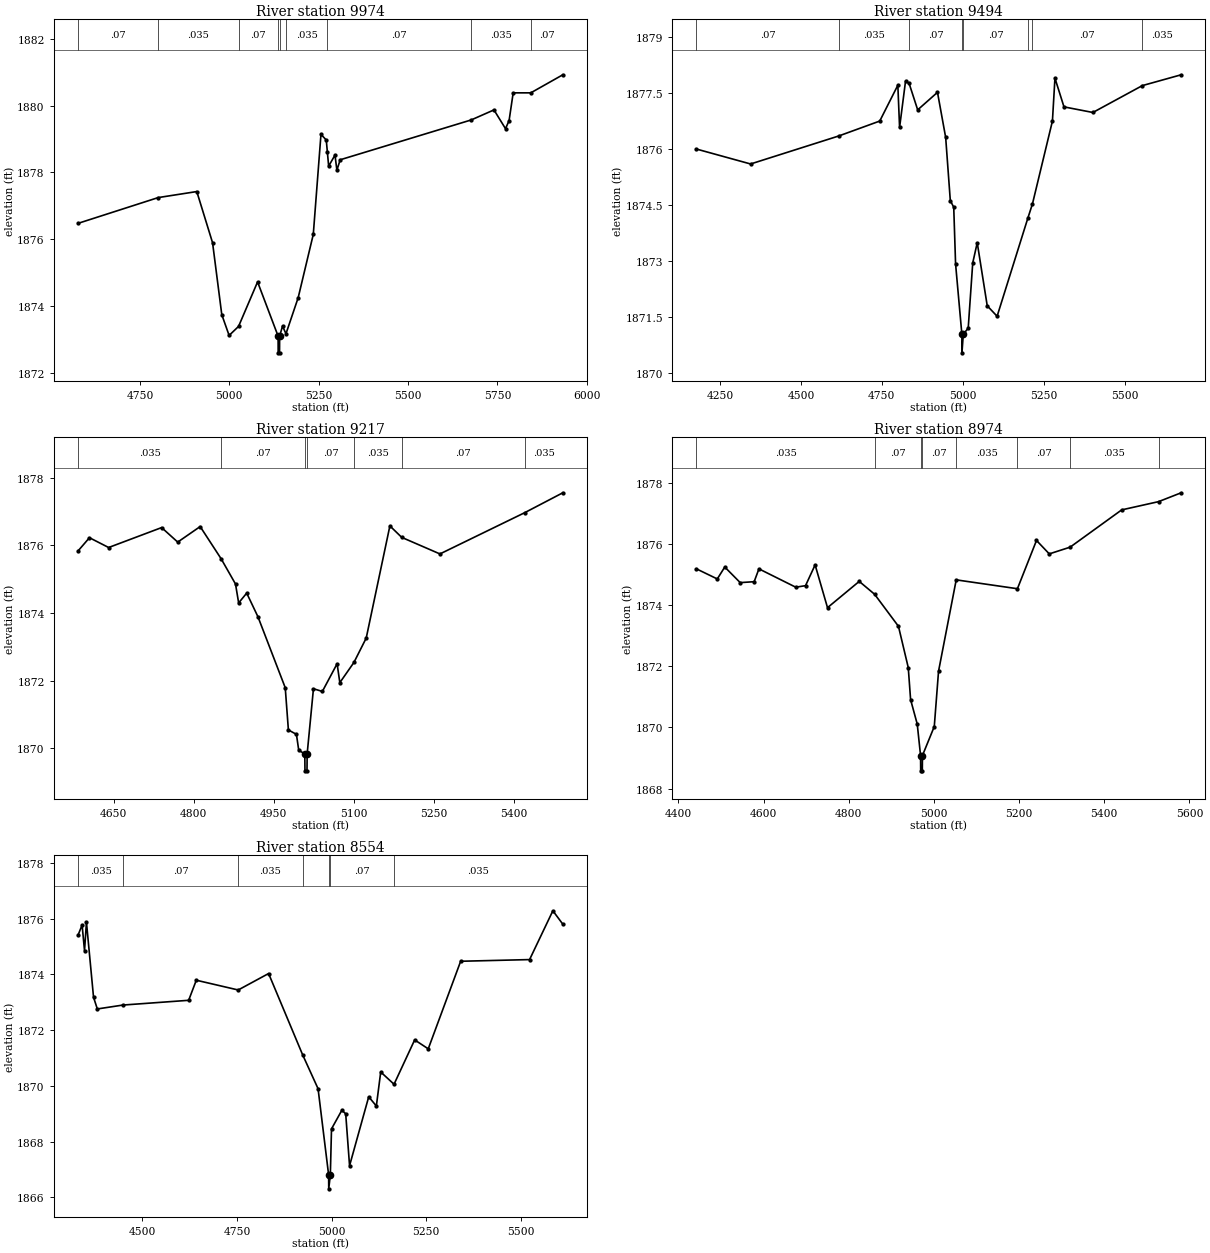
Type RM Length L Ch R = 1,9974,480,480,480
BEGIN DESCRIPTION:
Sweetwater Creek Trib 36 4090
END DESCRIPTION:
XS GIS Cut Line= 3
      1445042.21      6888331.60      1444903.51      6887932.09
      1444035.90      6887589.50
#Sta/Elev= 30
  4577.1 1876.48  4801.2 1877.25  4909.1 1877.43  4953.2 1875.90  4979.0 1873.75
  4999.5 1873.13  5025.9 1873.40  5079.1 1874.73  5136.5 1873.11  5136.7 1872.61
  5140.5 1872.61  5140.8 1873.11  5148.9 1873.41  5158.5 1873.18  5192.7 1874.26
  5234.9 1876.15  5256.4 1879.14  5271.2 1878.97  5274.3 1878.61  5277.9 1878.19
  5295.6 1878.52  5300.9 1878.07  5310.2 1878.38  5676.5 1879.57  5740.2 1879.87
  5772.5 1879.31  5782.5 1879.55  5794.0 1880.38  5843.2 1880.38  5932.8 1880.92
#Mann=9,-1,0
  4577.1    0.07       0  4801.2   0.035       0  5025.9    0.07       0
  5136.5   0.035       0  5140.8    0.07       0  5158.5   0.035       0
  5274.3    0.07       0  5676.5   0.035       0  5843.2    0.07       0
Bank Sta=5136.5,5140.8
Exp/Cntr=0.3,0.1

Type RM Length L Ch R = 1,9494,277,277,277
BEGIN DESCRIPTION:
Sweetwater Creek Trib 36 4087
END DESCRIPTION:
XS GIS Cut Line= 3
      1445203.24      6888495.23      1444922.56      6887721.79
      1444319.55      6887418.91
#Sta/Elev= 30
  4177.2 1875.99  4344.5 1875.59  4616.7 1876.34  4743.5 1876.74  4799.4 1877.70
  4804.8 1876.57  4823.2 1877.81  4834.2 1877.75  4860.7 1877.04  4921.9 1877.51
  4947.2 1876.30  4961.5 1874.61  4972.1 1874.43  4977.8 1872.91  4997.2 1871.03
  4997.5 1870.53  5001.6 1871.03  5016.8 1871.19  5030.8 1872.94  5044.7 1873.48
  5075.6 1871.79  5106.1 1871.51  5201.1 1874.14  5215.3 1874.52  5277.0 1876.74
  5284.8 1877.89  5312.7 1877.12  5402.0 1876.97  5554.8 1877.69  5674.8 1877.98
#Mann=8,-1,0
  4177.2    0.07       0  4616.7   0.035       0  4834.2    0.07       0
  4997.2    0.07       0  5001.6    0.07       0  5201.1   0.035       0
  5215.3    0.07       0  5554.8   0.035       0
Bank Sta=4997.2,5001.6
Exp/Cntr=0.3,0.1

Type RM Length L Ch R = 1,9217,243,243,243
BEGIN DESCRIPTION:
Sweetwater Creek Trib 36 4091
END DESCRIPTION:
XS GIS Cut Line= 3
      1445135.04      6887815.82      1444905.28      6887467.82
      1444423.83      6887365.05
#Sta/Elev= 30
  4583.0 1875.84  4604.3 1876.23  4640.3 1875.94  4739.7 1876.53  4769.9 1876.10
  4812.0 1876.56  4851.2 1875.61  4878.3 1874.86  4884.2 1874.30  4899.3 1874.59
  4920.4 1873.89  4971.6 1871.79  4977.5 1870.54  4992.6 1870.41  4996.9 1869.94
  5008.3 1869.83  5008.6 1869.33  5012.4 1869.33  5012.7 1869.83  5024.5 1871.76
  5041.2 1871.68  5068.9 1872.50  5074.0 1871.94  5100.5 1872.54  5123.5 1873.26
  5167.9 1876.58  5190.1 1876.24  5261.8 1875.75  5420.7 1876.97  5492.3 1877.56
#Mann=7,-1,0
  4583.0   0.035       0  4851.2    0.07       0  5008.3    0.07       0
  5012.7    0.07       0  5100.5   0.035       0  5190.1    0.07       0
  5420.7   0.035       0
Bank Sta=5008.3,5012.7
Exp/Cntr=0.3,0.1

Type RM Length L Ch R = 1,8974,420,420,420
BEGIN DESCRIPTION:
Sweetwater Creek Trib 36 4088
END DESCRIPTION:
XS GIS Cut Line= 3
      1445168.56      6887711.40      1444958.77      6887252.50
      1444325.25      6887252.37
#Sta/Elev= 30
  4442.4 1875.19  4491.3 1874.86  4508.9 1875.25  4545.1 1874.74  4577.9 1874.77
  4589.1 1875.19  4675.5 1874.59  4698.5 1874.64  4721.0 1875.32  4750.1 1873.92
  4824.6 1874.78  4860.6 1874.36  4916.7 1873.31  4939.7 1871.96  4945.2 1870.91
  4960.8 1870.11  4968.6 1869.08  4968.9 1868.58  4972.7 1868.58  4973.0 1869.08
  5000.8 1870.03  5010.8 1871.84  5052.3 1874.83  5196.0 1874.54  5240.8 1876.12
  5270.8 1875.68  5319.7 1875.90  5440.8 1877.12  5527.4 1877.39  5580.5 1877.68
#Mann=8,-1,0
  4442.4   0.035       0  4860.6    0.07       0  4968.6    0.07       0
  4973.0    0.07       0  5052.3   0.035       0  5196.0    0.07       0
  5319.7   0.035       0  5527.4    0.07       0
Bank Sta=4968.6,4973
Exp/Cntr=0.3,0.1

Type RM Length L Ch R = 1,8554,0,0,0
BEGIN DESCRIPTION:
Sweetwater Creek Trib 36 4089
END DESCRIPTION:
XS GIS Cut Line= 3
      1445211.93      6887668.54      1445141.80      6887002.42
      1444538.30      6886908.29
#Sta/Elev= 30
  4330.2 1875.41  4340.8 1875.77  4347.2 1874.85  4352.3 1875.87  4371.0 1873.18
  4381.0 1872.76  4448.9 1872.90  4622.3 1873.07  4642.5 1873.79  4753.2 1873.44
  4833.5 1874.03  4923.3 1871.12  4964.2 1869.90  4992.1 1866.81  4992.4 1866.31
  4996.6 1866.81  4999.7 1868.46  5027.1 1869.13  5037.2 1869.00  5047.4 1867.14
  5098.0 1869.61  5118.2 1869.28  5129.7 1870.50  5164.9 1870.06  5219.4 1871.65
  5255.3 1871.33  5340.9 1874.47  5523.0 1874.53  5584.5 1876.28  5610.8 1875.80
#Mann=7,-1,0
  4330.2   0.035       0  4448.9    0.07       0  4753.2   0.035       0
  4923.3    0.07       0  4992.1    0.07       0  4996.6    0.07       0
  5164.9   0.035       0
Bank Sta=4992.1,4996.6
Exp/Cntr=0.3,0.1

Chan Stop Cuts=-1