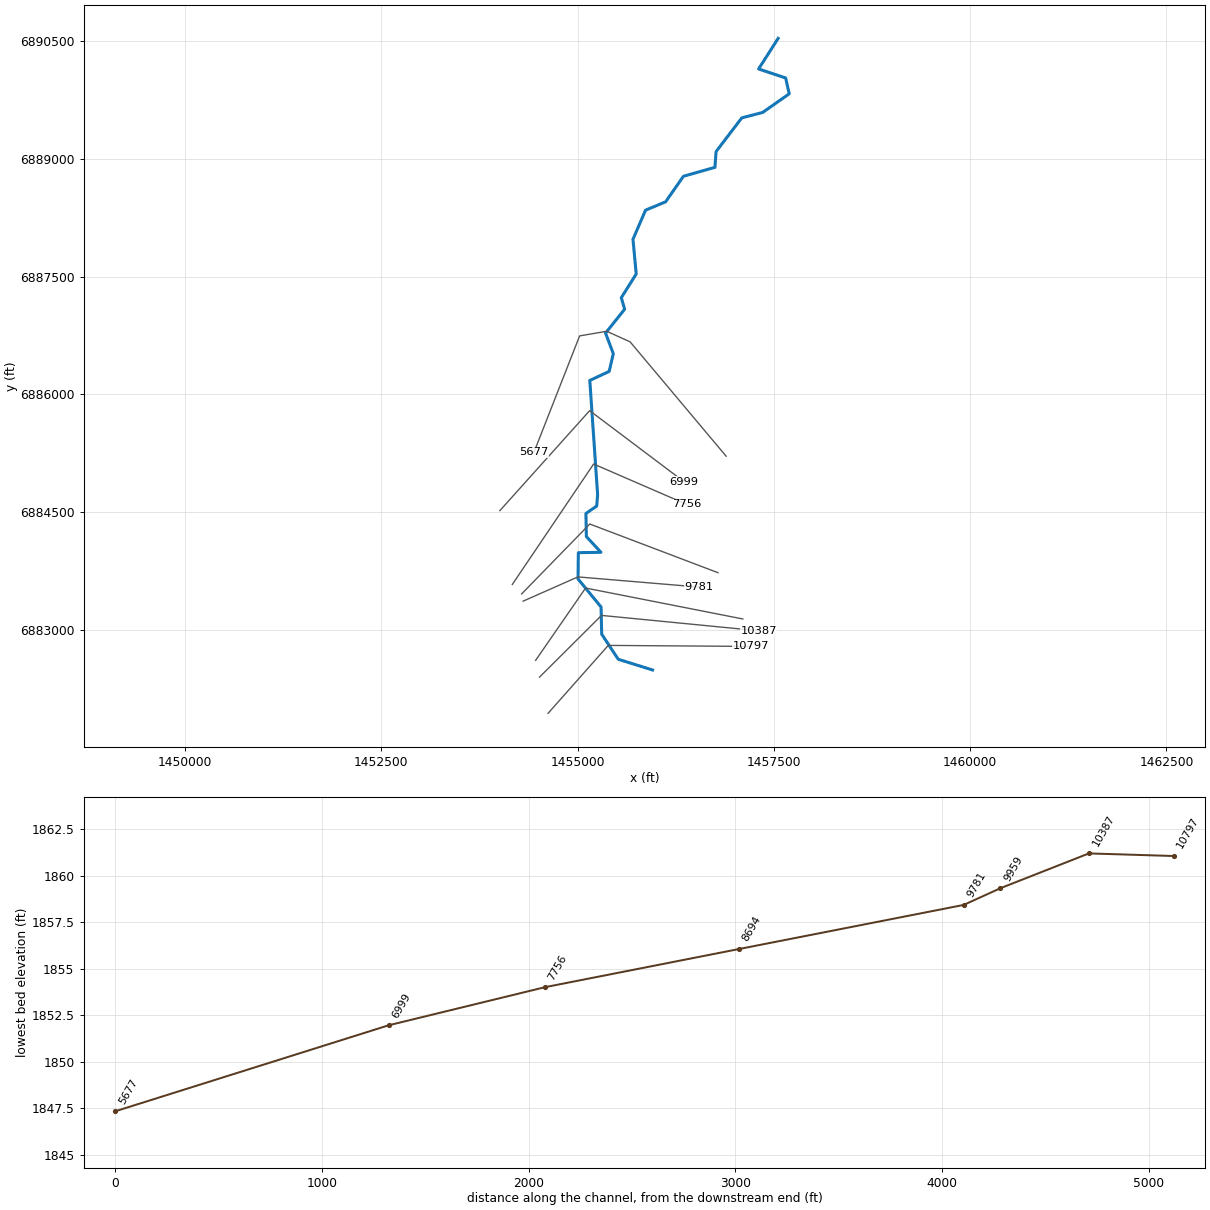
--- Sweetwater Creek Trib 38.prj (project) ---

Proj Title=Sweetwater Creek Trib 38 Base Level Engineering
Current Plan=p01
Default Exp/Contr=0.3,0.1
English Units
Geom File=g01
Flow File=f01
Plan File=p01
BEGIN DESCRIPTION:
Sweetwater Creek Trib 38
END DESCRIPTION:

--- Sweetwater Creek Trib 38.p01 (plan) ---

Plan Title=Multiple Run
Short Identifier=Multiple
Geom File=g01
Flow File=f01
Subcritical Flow
K Sum by GR= 0
Std Step Tol= 0.01
Critical Tol= 0.01
Num of Std Step Trials= 20
Max Error Tol= 0.3
Flow Tol Ratio= 0.001
Split Flow NTrial= 30
Split Flow Tol= 0.02
Split Flow Ratio= 0.02
Log Output Level= 0
Friction Slope Method= 1
Unsteady Friction Slope Method= 2
Unsteady Bridges Friction Slope Method= 1
Parabolic Critical Depth
Global Vel Dist=  1 , 1 , 1
Global Log Level= 0
CheckData=True
Encroach Param= -1, 0, 0, 0
BEGIN DESCRIPTION:
Multiple Run
END DESCRIPTION:

--- Sweetwater Creek Trib 38.f01 (steady flow) ---

Flow Title=Multiple
Number of Profiles=7
Profile Names=10-year,25-year,50-year,1pct_min,100-year,1pct_plu,500-year
River Rch & RM= Sweetwater Creek,Reach-1,10797
     391     550     683     421     839    1675    1284
Boundary for River Rch & Prof#=Sweetwater Creek,Reach-1,1
Up Type=0
Dn Type=3
Dn Slope=0.005
Boundary for River Rch & Prof#=Sweetwater Creek,Reach-1,2
Up Type=0
Dn Type=3
Dn Slope=0.005
Boundary for River Rch & Prof#=Sweetwater Creek,Reach-1,3
Up Type=0
Dn Type=3
Dn Slope=0.005
Boundary for River Rch & Prof#=Sweetwater Creek,Reach-1,4
Up Type=0
Dn Type=3
Dn Slope=0.005
Boundary for River Rch & Prof#=Sweetwater Creek,Reach-1,5
Up Type=0
Dn Type=3
Dn Slope=0.005
Boundary for River Rch & Prof#=Sweetwater Creek,Reach-1,6
Up Type=0
Dn Type=3
Dn Slope=0.005
Boundary for River Rch & Prof#=Sweetwater Creek,Reach-1,7
Up Type=0
Dn Type=3
Dn Slope=0.005

--- Sweetwater Creek Trib 38.g01 (geometry) ---

Geom Title=Existing Conditions

River Reach=Sweetwater Creek,Reach-1
Reach XY= 30
      1455955.00      6882488.00      1455518.46      6882624.37
      1455307.24      6882943.93      1455299.54      6883290.45
      1455006.21      6883647.59      1455010.00      6883983.01
      1455298.02      6883987.72      1455112.32      6884187.90
      1455106.54      6884482.15      1455243.89      6884577.68
      1455255.58      6884719.73      1455155.87      6886177.69
      1455402.91      6886293.24      1455455.18      6886519.57
      1455356.46      6886781.78      1455599.89      6887085.71
      1455556.80      6887231.89      1455746.96      6887534.68
      1455705.75      6887977.32      1455866.24      6888348.05
      1456121.67      6888454.63      1456348.54      6888780.26
      1456749.42      6888893.58      1456764.17      6889094.72
      1457091.78      6889524.38      1457357.45      6889593.47
      1457695.88      6889831.24      1457649.96      6890032.92
      1457305.62      6890147.66      1457555.00      6890538.00

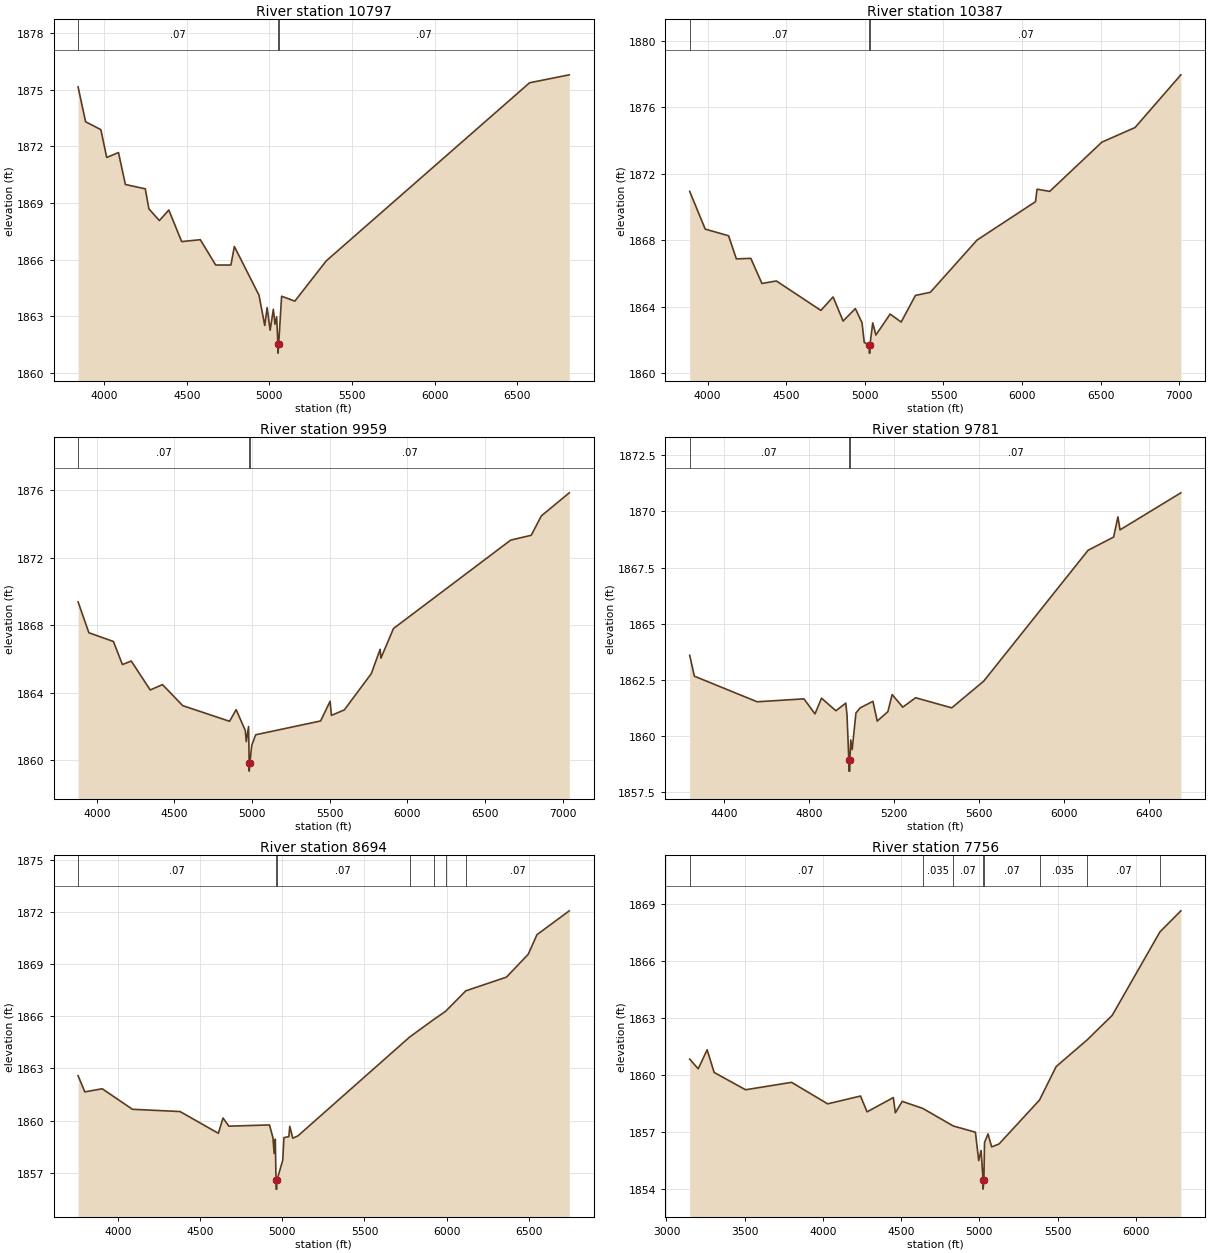
Type RM Length L Ch R = 1,10797,410,410,410
BEGIN DESCRIPTION:
Sweetwater Creek Trib 38 7.0
END DESCRIPTION:
XS GIS Cut Line= 3
      1454623.77      6881934.90      1455391.32      6882801.19
      1457204.97      6882788.00
#Sta/Elev= 30
  3842.6 1875.14  3887.8 1873.30  3980.3 1872.88  4015.8 1871.41  4086.9 1871.67
  4128.7 1869.98  4249.1 1869.75  4270.9 1868.69  4334.5 1868.07  4391.3 1868.63
  4469.1 1866.96  4582.0 1867.06  4674.9 1865.72  4766.9 1865.72  4787.8 1866.70
  4936.7 1864.13  4971.8 1862.52  4986.0 1863.47  5004.3 1862.27  5023.7 1863.38
  5033.7 1862.59  5043.7 1862.98  5051.3 1861.56  5051.7 1861.06  5056.0 1861.56
  5073.7 1864.07  5153.7 1863.81  5343.7 1865.94  6573.7 1875.36  6813.7 1875.78
#Mann=3,-1,0
  3842.6    0.07       0  5051.3    0.07       0  5056.0    0.07       0
Bank Sta=5051.3,5056
Exp/Cntr=0.3,0.1

Type RM Length L Ch R = 1,10387,428,428,428
BEGIN DESCRIPTION:
Sweetwater Creek Trib 38 6.0
END DESCRIPTION:
XS GIS Cut Line= 3
      1454515.92      6882397.34      1455305.06      6883183.48
      1457305.03      6882988.00
#Sta/Elev= 30
  3886.1 1870.93  3984.9 1868.66  4133.4 1868.26  4182.9 1866.87  4274.8 1866.90
  4345.5 1865.39  4437.5 1865.54  4720.3 1863.77  4798.1 1864.58  4861.7 1863.13
  4939.5 1863.88  4981.9 1863.03  4996.1 1861.84  5027.7 1861.70  5028.1 1861.20
  5032.1 1861.20  5032.4 1861.70  5050.2 1863.02  5070.3 1862.29  5160.7 1863.55
  5231.0 1863.07  5321.5 1864.67  5416.5 1864.86  5713.3 1868.00  6085.1 1870.31
  6095.1 1871.06  6175.5 1870.93  6507.1 1873.89  6718.1 1874.77  7009.5 1877.94
#Mann=3,-1,0
  3886.1    0.07       0  5027.7    0.07       0  5032.4    0.07       0
Bank Sta=5027.7,5032.4
Exp/Cntr=0.3,0.1

Type RM Length L Ch R = 1,9959,178,178,178
BEGIN DESCRIPTION:
Sweetwater Creek Trib 38 5.0
END DESCRIPTION:
XS GIS Cut Line= 3
      1454466.13      6882610.97      1455102.35      6883532.36
      1457104.99      6883138.00
#Sta/Elev= 30
  3880.3 1869.38  3949.6 1867.55  4107.6 1867.03  4165.5 1865.66  4222.3 1865.87
  4344.6 1864.15  4423.5 1864.47  4553.5 1863.22  4855.0 1862.29  4897.5 1862.98
  4956.4 1861.74  4962.5 1861.08  4977.4 1861.98  4981.1 1859.83  4981.4 1859.33
  4985.8 1859.83  4997.9 1860.87  5023.1 1861.49  5441.0 1862.31  5502.1 1863.48
  5510.7 1862.64  5593.8 1862.97  5767.1 1865.12  5824.0 1866.57  5829.1 1866.04
  5909.8 1867.80  6664.0 1873.05  6796.5 1873.34  6861.4 1874.49  7041.1 1875.86
#Mann=3,-1,0
  3880.3    0.07       0  4981.1    0.07       0  4985.8    0.07       0
Bank Sta=4981.1,4985.8
Exp/Cntr=0.3,0.1

Type RM Length L Ch R = 1,9781,1087,1087,1087
BEGIN DESCRIPTION:
Sweetwater Creek Trib 38 4.2
END DESCRIPTION:
XS GIS Cut Line= 3
      1454307.16      6883365.25      1455004.50      6883674.16
      1456550.57      6883544.46
#Sta/Elev= 30
  4237.3 1863.59  4259.4 1862.66  4555.1 1861.52  4775.6 1861.65  4827.7 1860.98
  4858.4 1861.68  4926.3 1861.12  4972.8 1861.46  4978.7 1860.91  4987.1 1858.93
  4987.5 1858.43  4991.7 1858.43  4992.1 1858.93  4996.1 1859.82  5002.8 1859.39
  5020.6 1861.02  5040.6 1861.25  5100.8 1861.54  5120.9 1860.66  5171.1 1861.08
  5191.2 1861.84  5241.3 1861.28  5301.6 1861.70  5472.1 1861.25  5622.7 1862.44
  6114.4 1868.27  6234.8 1868.86  6254.9 1869.76  6264.9 1869.18  6551.5 1870.83
#Mann=3,-1,0
  4237.3    0.07       0  4987.1    0.07       0  4992.1    0.07       0
Bank Sta=4987.1,4992.1
Exp/Cntr=0.3,0.1

Type RM Length L Ch R = 1,8694,938,938,938
BEGIN DESCRIPTION:
Sweetwater Creek Trib 38 4.1
END DESCRIPTION:
XS GIS Cut Line= 3
      1454287.72      6883457.38      1455155.49      6884348.17
      1456788.69      6883727.66
#Sta/Elev= 30
  3756.4 1862.58  3797.4 1861.65  3903.4 1861.83  4087.3 1860.65  4377.2 1860.52
  4610.5 1859.27  4638.8 1860.15  4674.3 1859.68  4921.7 1859.75  4943.0 1859.01
  4950.0 1858.11  4957.2 1858.93  4961.6 1856.56  4962.0 1856.06  4966.3 1856.06
  4966.7 1856.56  5002.4 1857.72  5009.7 1859.02  5039.8 1859.08  5045.2 1859.67
  5063.7 1858.99  5094.7 1859.12  5774.6 1864.80  5926.1 1865.84  5993.7 1866.28
  6117.3 1867.46  6364.7 1868.25  6497.1 1869.56  6550.6 1870.69  6747.1 1872.06
#Mann=7,-1,0
  3756.4    0.07       0  4961.6    0.07       0  4966.7    0.07       0
  5774.6   0.035       0  5926.1    0.07       0  5993.7   0.035       0
  6117.3    0.07       0
Bank Sta=4961.6,4966.7
Exp/Cntr=0.3,0.1

Type RM Length L Ch R = 1,7756,757,757,757
BEGIN DESCRIPTION:
Sweetwater Creek Trib 38 4.0
END DESCRIPTION:
XS GIS Cut Line= 3
      1454169.22      6883578.19      1455204.61      6885113.00
      1456385.94      6884599.79
#Sta/Elev= 30
  3148.6 1860.84  3203.1 1860.33  3260.1 1861.33  3305.0 1860.14  3505.9 1859.23
  3799.8 1859.62  4030.6 1858.49  4240.4 1858.90  4282.4 1858.07  4450.2 1858.82
  4463.2 1858.02  4507.2 1858.62  4638.6 1858.25  4832.7 1857.33  4974.9 1857.00
  4995.9 1855.51  5011.3 1856.04  5023.7 1854.51  5024.1 1854.01  5029.0 1854.51
  5033.1 1856.46  5055.3 1856.91  5078.7 1856.23  5125.7 1856.38  5384.5 1858.69
  5491.1 1860.45  5689.0 1861.85  5849.4 1863.14  6154.0 1867.52  6288.0 1868.63
#Mann=8,-1,0
  3148.6    0.07       0  4638.6   0.035       0  4832.7    0.07       0
  5023.7    0.07       0  5029.0    0.07       0  5384.5   0.035       0
  5689.0    0.07       0  6154.0   0.035       0
Bank Sta=5023.7,5029
Exp/Cntr=0.3,0.1

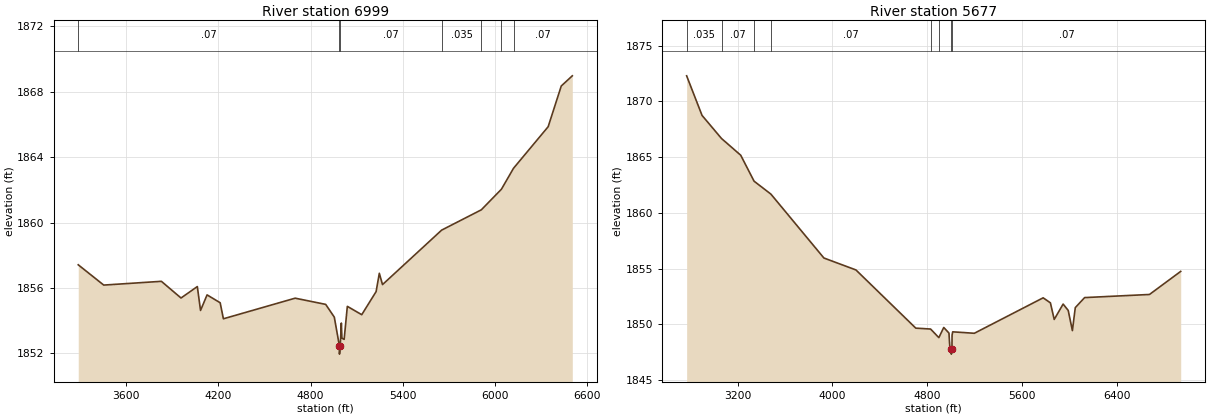
Type RM Length L Ch R = 1,6999,1322,1322,1322
BEGIN DESCRIPTION:
Sweetwater Creek Trib 38 2599
END DESCRIPTION:
XS GIS Cut Line= 3
      1454010.26      6884518.16      1455154.26      6885793.04
      1456354.98      6884888.01
#Sta/Elev= 30
  3287.1 1857.42  3453.1 1856.18  3828.4 1856.41  3956.2 1855.39  4062.4 1856.09
  4083.3 1854.63  4125.9 1855.58  4211.1 1855.10  4232.1 1854.12  4699.3 1855.38
  4898.1 1855.00  4954.2 1854.22  4987.4 1852.46  4987.8 1851.96  4992.7 1852.46
  5000.0 1853.86  5003.6 1852.94  5018.2 1852.86  5039.0 1854.88  5132.7 1854.37
  5226.3 1855.78  5247.2 1856.90  5268.0 1856.21  5653.1 1859.54  5911.3 1860.78
  6042.2 1862.04  6120.9 1863.32  6346.4 1865.86  6431.8 1868.35  6503.6 1868.97
#Mann=7,-1,0
  3287.1    0.07       0  4987.4    0.07       0  4992.7    0.07       0
  5653.1   0.035       0  5911.3    0.07       0  6042.2   0.035       0
  6120.9    0.07       0
Bank Sta=4987.4,4992.7
Exp/Cntr=0.3,0.1

Type RM Length L Ch R = 1,5677,0,0,0
BEGIN DESCRIPTION:
Sweetwater Creek Trib 38 4122
END DESCRIPTION:
XS GIS Cut Line= 5
      1456892.56      6885212.26      1455669.23      6886669.85
      1455371.08      6886804.83      1455026.32      6886745.59
      1454445.28      6885263.64
#Sta/Elev= 30
  2769.8 1872.30  2899.8 1868.75  3064.1 1866.68  3226.3 1865.18  3339.2 1862.85
  3481.4 1861.69  3928.8 1855.96  4199.3 1854.89  4704.7 1849.67  4829.6 1849.59
  4899.3 1848.82  4940.8 1849.73  4984.7 1849.23  4992.9 1847.84  5004.4 1847.84
  5004.8 1847.34  5009.9 1847.84  5011.0 1849.04  5016.3 1849.34  5199.0 1849.21
  5780.1 1852.39  5841.3 1851.94  5873.5 1850.45  5948.7 1851.83  5991.7 1851.26
  6027.0 1849.45  6051.4 1851.51  6130.1 1852.41  6677.9 1852.69  6941.6 1854.76
#Mann=8,-1,0
  2769.8   0.035       0  3064.1    0.07       0  3339.2   0.035       0
  3481.4    0.07       0  4829.6    0.16       0  4899.3    0.07       0
  5004.4    0.07       0  5009.9    0.07       0
Bank Sta=5004.4,5009.9
Exp/Cntr=0.3,0.1

Chan Stop Cuts=-1