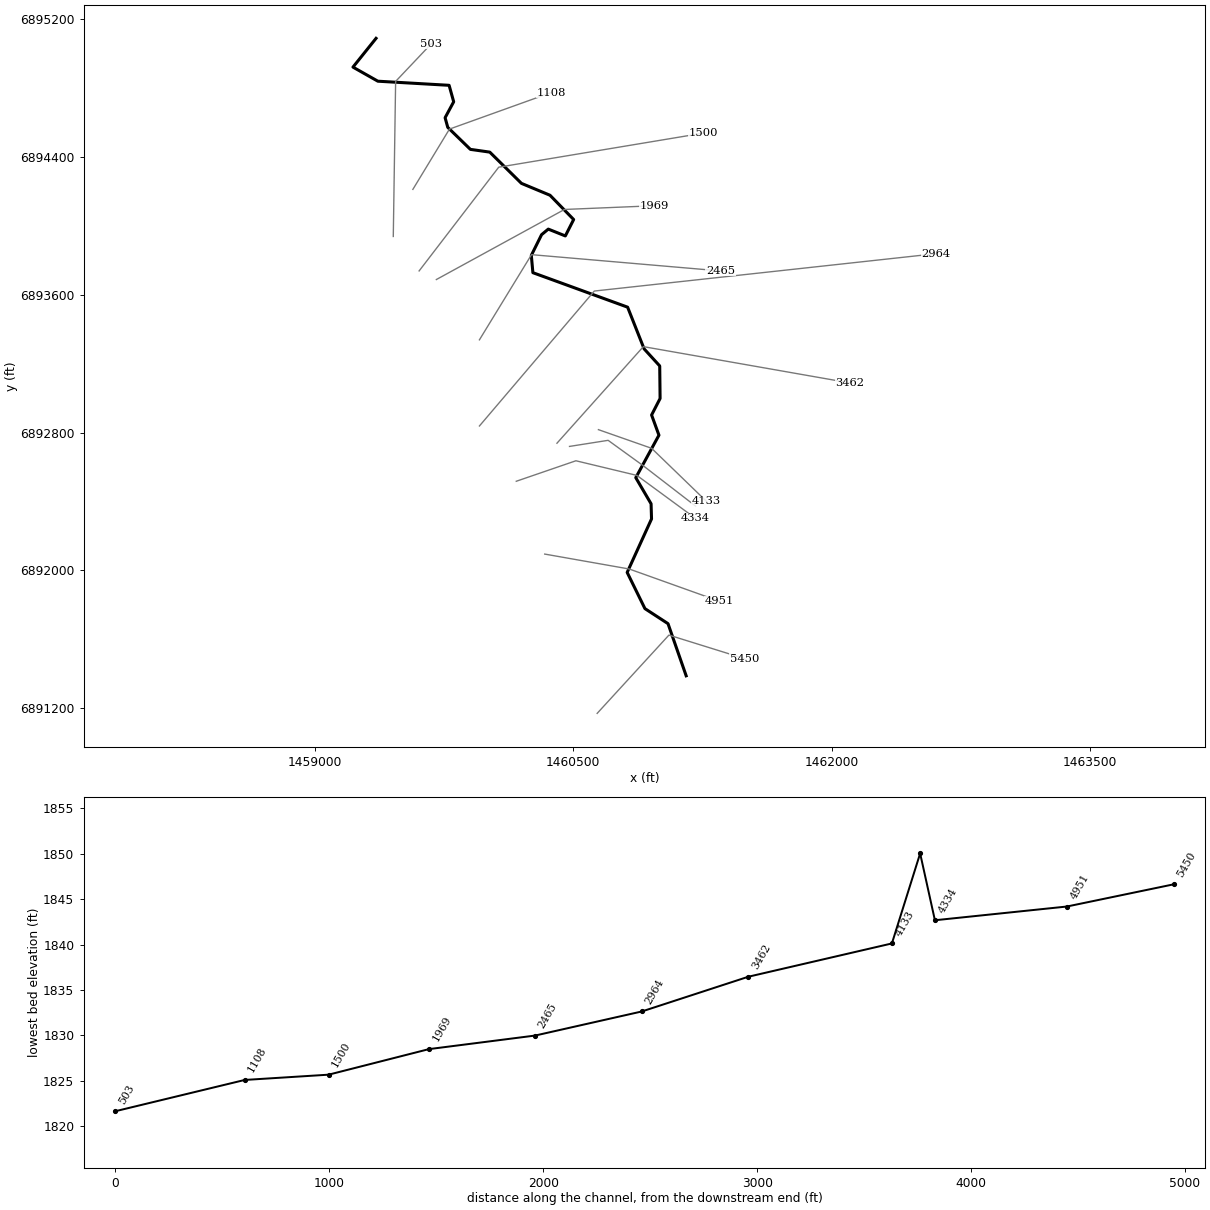
--- Sweetwater Creek Trib 39.prj (project) ---

Proj Title=Sweetwater Creek Trib 39 Base Level Engineering
Current Plan=p01
Default Exp/Contr=0.3,0.1
English Units
Geom File=g01
Flow File=f01
Plan File=p01
Y Axis Title=Elevation
X Axis Title(PF)=Main Channel Distance
X Axis Title(XS)=Station
BEGIN DESCRIPTION:
Sweetwater Creek Trib 39
END DESCRIPTION:
DSS Export Rating Curves= 0
DSS Export Rating Curve Sorted= 0
DSS Export Volume Flow Curves= 0
DXF OffsetX= 0
DXF OffsetY= 0
DXF ScaleX= 1
DXF ScaleY= 10

--- Sweetwater Creek Trib 39.p01 (plan) ---

Plan Title=Multiple Run
Short Identifier=Multiple
Geom File=g01
Flow File=f01
Subcritical Flow
K Sum by GR= 0
Std Step Tol= 0.01
Critical Tol= 0.01
Num of Std Step Trials= 20
Max Error Tol= 0.3
Flow Tol Ratio= 0.001
Split Flow NTrial= 30
Split Flow Tol= 0.02
Split Flow Ratio= 0.02
Log Output Level= 0
Friction Slope Method= 1
Unsteady Friction Slope Method= 2
Unsteady Bridges Friction Slope Method= 1
Parabolic Critical Depth
Global Vel Dist=  1 , 1 , 1
Global Log Level= 0
CheckData=True
Encroach Param= -1, 0, 0, 0
BEGIN DESCRIPTION:
Multiple Run
END DESCRIPTION:

--- Sweetwater Creek Trib 39.f01 (steady flow) ---

Flow Title=Multiple
Number of Profiles=7
Profile Names=10-year,25-year,50-year,1pct_min,100-year,1pct_plu,500-year
River Rch & RM= Sweetwater Creek,Reach-1,5450
     482     695     877     550    1097    2189    1738
Boundary for River Rch & Prof#=Sweetwater Creek,Reach-1,1
Up Type=0
Dn Type=3
Dn Slope=0.005
Boundary for River Rch & Prof#=Sweetwater Creek,Reach-1,2
Up Type=0
Dn Type=3
Dn Slope=0.005
Boundary for River Rch & Prof#=Sweetwater Creek,Reach-1,3
Up Type=0
Dn Type=3
Dn Slope=0.005
Boundary for River Rch & Prof#=Sweetwater Creek,Reach-1,4
Up Type=0
Dn Type=3
Dn Slope=0.005
Boundary for River Rch & Prof#=Sweetwater Creek,Reach-1,5
Up Type=0
Dn Type=3
Dn Slope=0.005
Boundary for River Rch & Prof#=Sweetwater Creek,Reach-1,6
Up Type=0
Dn Type=3
Dn Slope=0.005
Boundary for River Rch & Prof#=Sweetwater Creek,Reach-1,7
Up Type=0
Dn Type=3
Dn Slope=0.005

--- Sweetwater Creek Trib 39.g01 (geometry) ---

Geom Title=Existing Conditions
Program Version=4.10

River Reach=Sweetwater Creek,Reach-1
Reach XY= 30
        1461155.        6891388.      1461049.58      6891690.67
      1460915.63        6891778.      1460812.53      6891987.99
      1460953.92      6892298.54      1460951.33      6892386.42
      1460862.53      6892537.99      1460996.97      6892784.65
      1460954.29      6892901.69      1461003.62      6892997.66
      1461001.45      6893186.53      1460910.85      6893285.71
      1460815.12      6893527.62      1460265.28      6893727.84
      1460256.24       6893828.3      1460315.75      6893948.41
       1460354.7      6893980.74      1460453.63      6893941.07
      1460501.92      6894036.32      1460364.68      6894177.24
      1460198.95      6894246.16      1460015.08      6894427.56
      1459902.58      6894443.52      1459771.22      6894571.32
      1459755.72      6894627.29      1459805.66      6894719.78
      1459779.05      6894815.34       1459365.5       6894839.2
      1459221.03      6894920.95        1459355.        6895088.

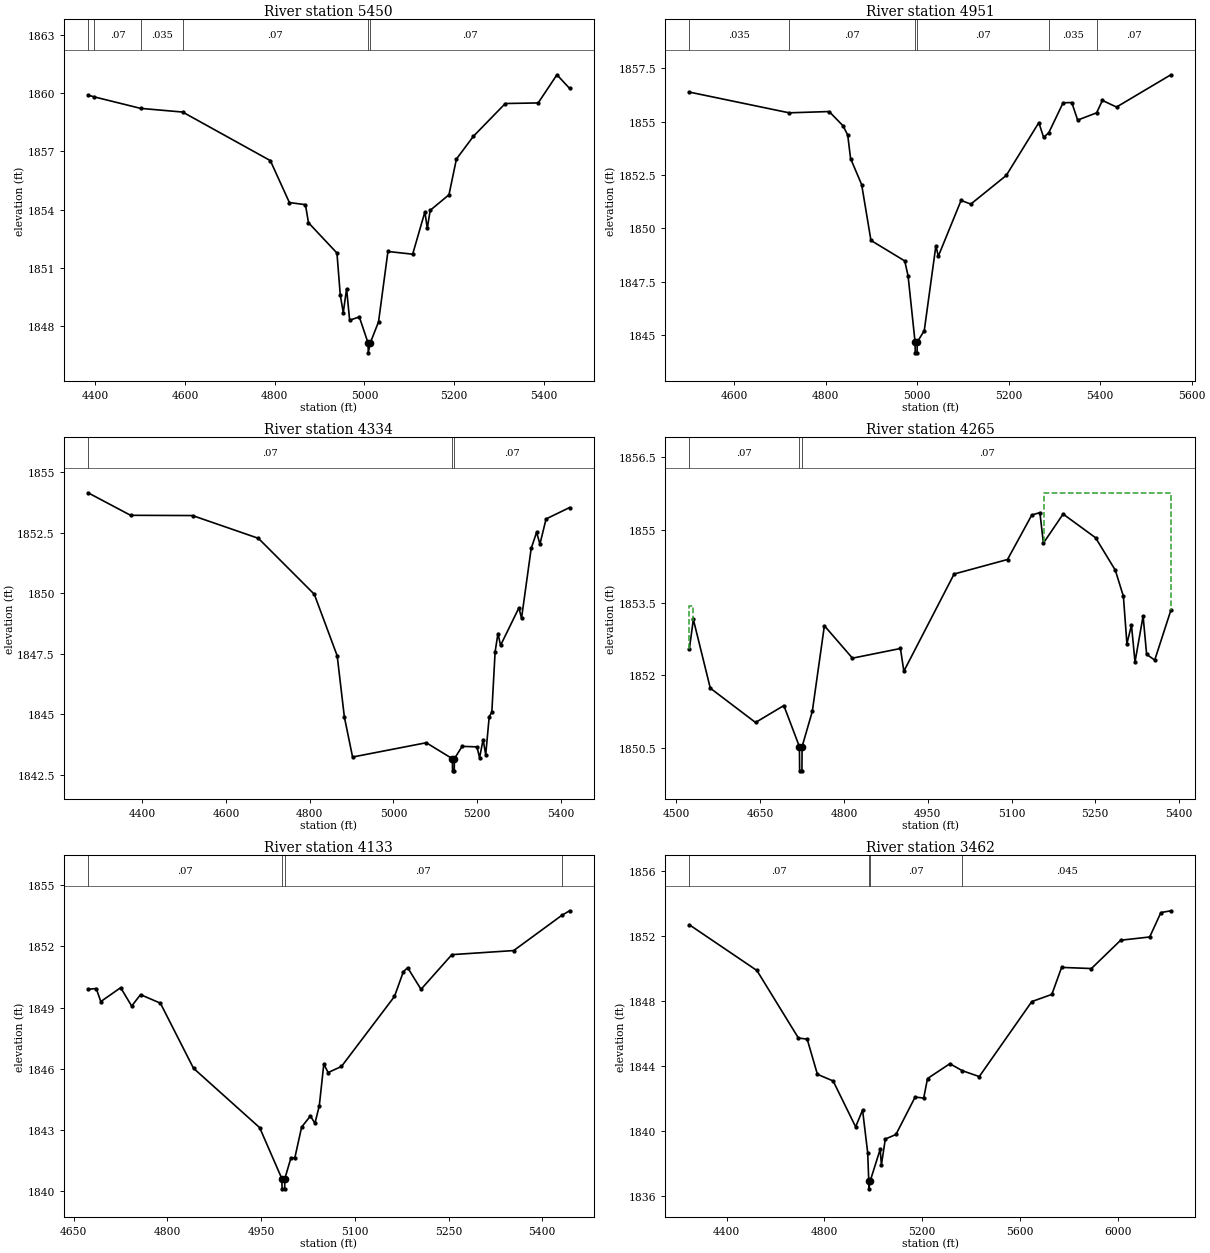
Type RM Length L Ch R = 1 ,5450    ,499,499,499
BEGIN DESCRIPTION:
Sweetwater Creek Trib 39 9.0
END DESCRIPTION:
XS GIS Cut Line= 3
      1460638.36      6891169.94      1461054.88      6891624.32
      1461491.88      6891488.26
#Sta/Elev= 30
  4383.6 1859.89  4397.7  1859.8  4500.8 1859.21  4594.6 1859.02  4790.2 1856.52
  4832.7 1854.36  4868.5 1854.25  4875.3 1853.32  4938.8 1851.76  4946.2  1849.6
  4952.9 1848.69  4960.3 1849.92  4967.1  1848.3  4988.7 1848.47  5008.3 1847.12
  5008.6 1846.62    5013 1847.12  5031.6 1848.22  5052.5 1851.84  5107.7  1851.7
    5135 1853.88  5140.3 1853.03  5146.8 1853.96  5188.7 1854.76  5205.3  1856.6
  5243.1 1857.77  5314.3 1859.46  5387.7 1859.49  5429.5 1860.94  5457.7 1860.24
#Mann= 6 ,-1 , 0
  4383.6    .035       0  4397.7     .07       0  4500.8    .035       0
  4594.6     .07       0  5008.3     .07       0    5013     .07       0
Bank Sta=5008.3,5013
XS Rating Curve= 0 ,0
Exp/Cntr=0.3,0.1

Type RM Length L Ch R = 1 ,4951    ,617,617,617
BEGIN DESCRIPTION:
Sweetwater Creek Trib 39 8.0
END DESCRIPTION:
XS GIS Cut Line= 3
      1460333.97      6892094.56      1460824.76      6892007.83
      1461346.88      6891821.12
#Sta/Elev= 30
  4501.6 1856.38  4719.8 1855.41  4807.3 1855.47  4837.8  1854.8  4847.9 1854.37
  4854.2 1853.27  4878.4 1852.05  4898.7 1849.44  4972.6 1848.48  4979.9 1847.78
  4995.2 1844.68  4995.6 1844.18  4999.6 1844.18  4999.9 1844.68  5015.3 1845.22
  5040.7 1849.19    5046  1848.7  5095.8 1851.31  5117.1 1851.14  5194.6 1852.48
  5265.8 1854.95  5276.3 1854.26  5287.6 1854.48  5318.9 1855.88  5337.9 1855.89
  5350.7 1855.07  5392.2 1855.41  5404.8 1855.99  5435.7 1855.68  5554.5 1857.19
#Mann= 6 ,-1 , 0
  4501.6    .035       0  4719.8     .07       0  4995.2     .07       0
  4999.9     .07       0  5287.6    .035       0  5392.2     .07       0
Bank Sta=4995.2,4999.9
XS Rating Curve= 0 ,0
Exp/Cntr=0.3,0.1

Type RM Length L Ch R = 1 ,4334    ,69,69,69
BEGIN DESCRIPTION:
Sweetwater Creek Trib 39 7.0
END DESCRIPTION:
XS GIS Cut Line= 5
      1460168.84      6892517.16      1460515.03      6892636.12
      1460868.93      6892551.21      1461208.39       6892302.2
1461208.527011866892302.09949531
#Sta/Elev= 30
    4270 1854.15  4371.7 1853.22  4519.7 1853.21  4677.2 1852.27  4810.9 1849.96
  4865.6 1847.42  4882.8 1844.89  4902.4 1843.24  5078.6 1843.83    5141 1843.17
  5141.4 1842.67  5145.5 1842.67  5145.8 1843.17  5164.3 1843.68  5199.8 1843.66
    5206 1843.21  5214.5 1843.96  5220.7 1843.34  5229.1 1844.91  5235.3 1845.09
  5243.2 1847.59    5250 1848.34  5256.2 1847.85  5300.1  1849.4  5306.3 1848.97
  5329.4 1851.85  5342.4 1852.52  5350.3 1852.03    5365 1853.07 5421.17 1853.54
#Mann= 3 ,-1 , 0
    4270     .07       0    5141     .07       0  5145.8     .07       0
Bank Sta=5141,5145.8
XS Rating Curve= 0 ,0
Exp/Cntr=0.3,0.1

Type RM Length L Ch R = 1 ,4265    ,132,132,132
BEGIN DESCRIPTION:
Sweetwater Creek Trib 39 4167
END DESCRIPTION:
XS GIS Cut Line= 4
      1460477.91      6892719.43        1460702.      6892754.75
      1460904.59       6892608.2       1461209.7       6892372.9
#Sta/Elev= 30
  4523.1 1852.54  4530.3 1853.15  4560.6 1851.73  4641.6 1851.02  4692.3 1851.37
  4720.2 1850.52  4720.6 1850.02  4724.7 1850.02    4725 1850.52  4743.3 1851.25
  4764.9 1853.02  4815.2 1852.35  4901.1 1852.55  4907.2 1852.08  4997.2 1854.09
  5092.8 1854.39  5136.3 1855.31  5150.8 1855.36  5157.1 1854.73  5192.4 1855.33
  5250.5 1854.84  5285.8 1854.17  5300.3 1853.63  5306.6 1852.65  5314.8 1853.03
  5321.1 1852.27  5335.6 1853.22  5341.9 1852.43  5356.4 1852.31  5385.3 1853.34
#Mann= 3 ,-1 , 0
  4523.1     .07       0  4720.2     .07       0    4725     .07       0
#XS Ineff= 2 , 0
         4529.95 1853.43 5158.38         1855.77
Permanent Ineff=
       F       F
Bank Sta=4720.2,4725
XS Rating Curve= 0 ,0
Exp/Cntr=0.3,0.1

Type RM Length L Ch R = 1 ,4133    ,671,671,671
BEGIN DESCRIPTION:
Sweetwater Creek Trib 39 6.0
END DESCRIPTION:
XS GIS Cut Line= 3
      1460645.75      6892816.69      1460954.43      6892708.47
      1461273.33      6892399.98
#Sta/Elev= 30
  4672.9  1849.9    4686 1849.94  4693.3  1849.3  4725.1 1849.98  4742.7 1849.08
  4756.9 1849.64  4788.7 1849.22  4841.7 1846.03  4947.6 1843.12  4983.1 1840.62
  4983.5 1840.12  4987.6 1840.12  4987.9 1840.62  4997.7 1841.64  5003.9 1841.64
  5014.8 1843.15  5028.9 1843.69  5036.1 1843.33  5043.1  1844.2  5050.3 1846.24
  5057.2 1845.82  5078.6 1846.12  5163.4 1849.55  5177.6 1850.76  5184.5 1850.96
  5205.9  1849.9  5255.3  1851.6  5354.3  1851.8    5431 1853.52  5443.7 1853.75
#Mann= 4 ,-1 , 0
  4672.9     .07       0  4983.1     .07       0  4987.9     .07       0
    5431    .045       0
Bank Sta=4983.1,4987.9
XS Rating Curve= 0 ,0
Exp/Cntr=0.3,0.1

Type RM Length L Ch R = 1 ,3462    ,498,498,498
BEGIN DESCRIPTION:
Sweetwater Creek Trib 39 5.0
END DESCRIPTION:
XS GIS Cut Line= 3
        1460405.        6892738.      1460906.51      6893298.62
      1462105.04      6893087.99
#Sta/Elev= 30
  4247.8 1852.69  4524.1 1849.88  4693.8 1845.73  4729.7 1845.66  4771.5  1843.5
  4835.9 1843.09  4927.8 1840.27  4956.2  1841.3  4977.1 1838.68  4981.5 1836.96
    4982 1836.46  4987.8 1836.96  5028.2 1838.89  5033.2 1837.93  5049.2 1839.52
  5092.6  1839.8  5171.1  1842.1  5206.2 1842.04  5221.8 1843.24  5313.2 1844.15
  5364.2 1843.72  5433.4 1843.36  5648.3 1847.97  5730.2 1848.41  5770.1 1850.07
    5892    1850  6011.7 1851.74  6130.4 1851.94  6176.2 1853.44  6216.9 1853.55
#Mann= 4 ,-1 , 0
  4247.8     .07       0  4981.5     .07       0  4987.8     .07       0
  5364.2    .045       0
Bank Sta=4981.5,4987.8
XS Rating Curve= 0 ,0
Exp/Cntr=0.3,0.1

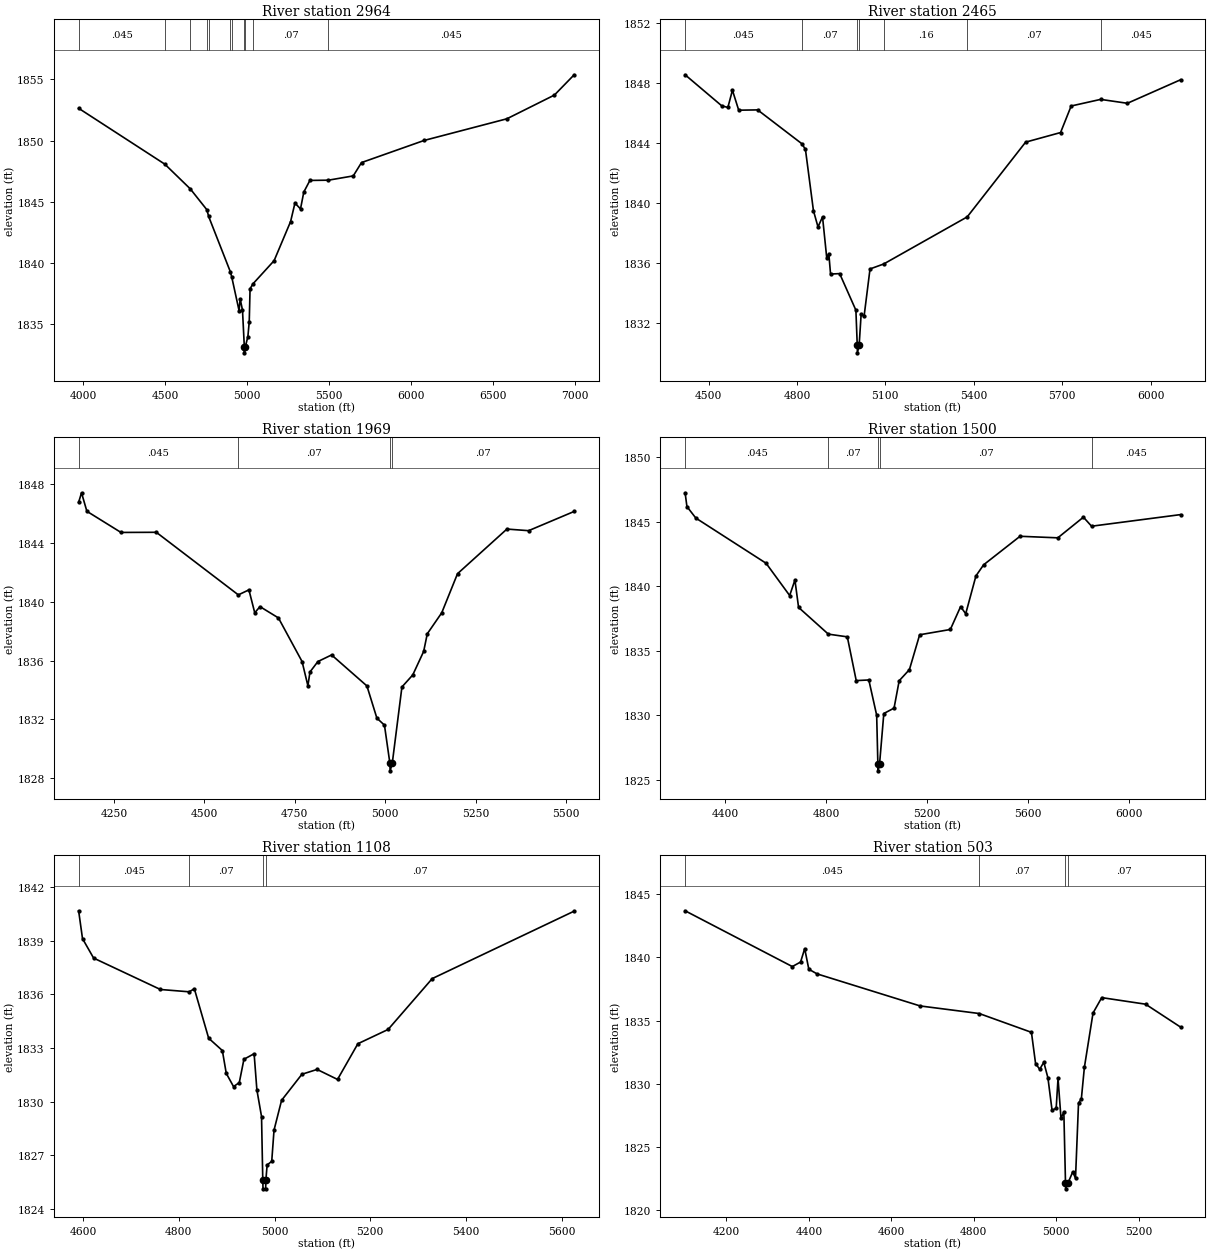
Type RM Length L Ch R = 1 ,2964    ,499,499,499
BEGIN DESCRIPTION:
Sweetwater Creek Trib 39 4.0
END DESCRIPTION:
XS GIS Cut Line= 3
      1459955.01      6892838.01      1460621.67      6893621.19
      1462604.96        6893838.
#Sta/Elev= 30
  3971.5 1852.64  4497.4 1848.07  4652.7 1846.05  4754.1 1844.34  4764.9 1843.79
  4896.6 1839.29  4905.3 1838.87  4950.5 1836.09  4957.1 1837.05  4971.3 1836.14
  4982.5 1833.14    4983 1832.64  4988.8 1833.14  5004.2 1833.97  5012.5 1835.18
  5017.5 1837.88  5035.7 1838.29  5164.3 1840.18  5264.9 1843.38  5291.4 1844.89
  5325.3 1844.41  5345.4 1845.79  5382.7 1846.74  5495.4 1846.76  5647.2 1847.11
  5697.5  1848.2  6079.7 1850.01  6584.4 1851.78  6874.4 1853.72  6995.1 1855.38
#Mann= 11 ,-1 , 0
  3971.5    .045       0  4497.4     .07       0  4652.7     .16       0
  4754.1     .07       0  4764.9     .16       0  4896.6     .07       0
  4905.3     .16       0  4982.5     .07       0  4988.8     .16       0
  5035.7     .07       0  5495.4    .045       0
Bank Sta=4982.5,4988.8
XS Rating Curve= 0 ,0
Exp/Cntr=0.3,0.1

Type RM Length L Ch R = 1 ,2465    ,496,496,496
BEGIN DESCRIPTION:
Sweetwater Creek Trib 39 3.0
END DESCRIPTION:
XS GIS Cut Line= 3
        1459955.      6893338.01      1460257.26      6893832.44
        1461355.        6893738.
#Sta/Elev= 30
  4420.5 1848.52  4544.3 1846.46  4565.6 1846.34  4581.1 1847.49  4602.4 1846.16
  4666.6 1846.18  4816.3 1843.93  4828.8 1843.55  4855.9 1839.47  4871.4 1838.38
  4886.8 1839.05    4901 1836.33  4908.1  1836.6    4914 1835.24  4944.9 1835.27
    5000 1832.83  5004.6 1830.49  5005.1 1829.99    5011 1830.49  5017.8 1832.57
  5027.8 1832.43  5047.9 1835.58  5094.2 1835.91  5377.7 1839.05  5575.8 1844.03
  5694.4 1844.67  5730.4 1846.44  5830.3 1846.88  5921.1 1846.62  6101.8 1848.19
#Mann= 7 ,-1 , 0
  4420.5    .045       0  4816.3     .07       0  5004.6     .07       0
    5011     .07       0  5094.2     .16       0  5377.7     .07       0
  5830.3    .045       0
Bank Sta=5004.6,5011
XS Rating Curve= 0 ,0
Exp/Cntr=0.3,0.1

Type RM Length L Ch R = 1 ,1969    ,469,469,469
BEGIN DESCRIPTION:
Sweetwater Creek Trib 39 2.0
END DESCRIPTION:
XS GIS Cut Line= 3
      1459705.02      6893688.01      1460448.54      6894094.75
      1460970.89      6894116.45
#Sta/Elev= 30
  4152.5 1846.78  4160.5 1847.43  4175.3 1846.17  4269.6 1844.73  4367.3 1844.74
  4594.1 1840.48  4623.4 1840.82  4639.5 1839.26    4654 1839.68    4705 1838.91
  4770.4 1835.94  4786.5 1834.29  4792.2 1835.23  4814.1 1835.94    4852 1836.39
  4949.7 1834.28  4977.2 1832.09  4998.2 1831.61  5013.3    1829  5013.8  1828.5
  5019.7    1829  5046.5 1834.21  5076.5 1835.03  5106.6 1836.63  5116.6 1837.83
  5156.6 1839.26  5200.2 1841.92  5336.8 1844.96  5396.8 1844.85  5522.8 1846.16
#Mann= 4 ,-1 , 0
  4152.5    .045       0  4594.1     .07       0  5013.3     .07       0
  5019.7     .07       0
Bank Sta=5013.3,5019.7
XS Rating Curve= 0 ,0
Exp/Cntr=0.3,0.1

Type RM Length L Ch R = 1 ,1500    ,392,392,392
BEGIN DESCRIPTION:
Sweetwater Creek Trib 39 1.0
END DESCRIPTION:
XS GIS Cut Line= 3
      1459604.99      6893737.99      1460067.04      6894340.14
      1461254.98        6894538.
#Sta/Elev= 30
    4241 1847.23  4248.3 1846.16  4283.6 1845.27  4561.9 1841.77  4655.3 1839.27
  4676.1 1840.47  4690.6 1838.35  4808.5 1836.28  4883.7 1836.07    4919 1832.68
  4968.9 1832.73    5000    1830  5004.8 1826.19  5005.3 1825.69  5011.3 1826.19
  5028.3 1830.13  5068.9 1830.55  5089.2 1832.67  5129.7 1833.53  5170.3 1836.23
  5291.9 1836.64  5332.5 1838.41  5352.8 1837.86  5393.3 1840.79  5423.7 1841.65
    5568 1843.86  5717.7 1843.74  5819.1 1845.34  5851.4 1844.64  6204.3 1845.54
#Mann= 5 ,-1 , 0
    4241    .045       0  4808.5     .07       0  5004.8     .07       0
  5011.3     .07       0  5851.4    .045       0
Bank Sta=5004.8,5011.3
XS Rating Curve= 0 ,0
Exp/Cntr=0.3,0.1

Type RM Length L Ch R = 1 ,1108    ,605,605,605
BEGIN DESCRIPTION:
Sweetwater Creek Trib 39 3926
END DESCRIPTION:
XS GIS Cut Line= 3
      1459568.68      6894211.28      1459781.04      6894561.18
      1460370.38      6894772.84
#Sta/Elev= 30
  4590.7 1840.69  4598.8 1839.13    4622 1838.04  4761.6 1836.28  4821.7 1836.15
  4832.5 1836.32  4862.4 1833.55    4891 1832.86  4899.2 1831.58  4914.4 1830.84
  4926.4 1831.06  4936.1 1832.37  4957.4 1832.68  4963.2 1830.65  4972.9 1829.16
  4975.5 1825.61    4976 1825.11  4981.5 1825.11    4982 1825.61  4984.6 1826.45
  4994.2 1826.65    4999  1828.4  5014.8 1830.07  5057.3 1831.53    5089  1831.8
  5131.7 1831.24  5174.2 1833.24  5237.4 1834.04  5329.6 1836.89  5626.2 1840.67
#Mann= 4 ,-1 , 0
  4590.7    .045       0  4821.7     .07       0  4975.5     .07       0
    4982     .07       0
Bank Sta=4975.5,4982
XS Rating Curve= 0 ,0
Exp/Cntr=0.3,0.1

Type RM Length L Ch R = 1 ,503     ,0,0,0
BEGIN DESCRIPTION:
Sweetwater Creek Trib 39 2605
END DESCRIPTION:
XS GIS Cut Line= 3
        1459455.      6893937.96      1459468.62      6894837.96
      1459676.24      6895057.13
#Sta/Elev= 30
  4099.9  1843.7    4360 1839.28    4380 1839.64    4390  1840.7    4400 1839.07
    4420  1838.7    4670 1836.16  4813.3 1835.56    4940 1834.07    4950  1831.6
    4960 1831.14    4970  1831.7    4980 1830.46    4990  1827.9    5000 1828.05
  5004.5 1830.42  5011.7 1827.25  5018.6 1827.77  5022.6 1822.17  5023.1 1821.67
  5029.2 1822.17  5040.1 1823.01  5046.9 1822.51  5054.2 1828.46  5061.1 1828.81
  5068.4 1831.29  5089.4  1835.6  5110.5 1836.82  5216.8  1836.3  5301.9 1834.48
#Mann= 4 ,-1 , 0
  4099.9    .045       0  4813.3     .07       0  5022.6     .07       0
  5029.2     .07       0
Bank Sta=5022.6,5029.2
XS Rating Curve= 0 ,0
Exp/Cntr=0.3,0.1

Chan Stop Cuts=-1
Use User Specified Reach Order=0
Composite Channel Slope=5