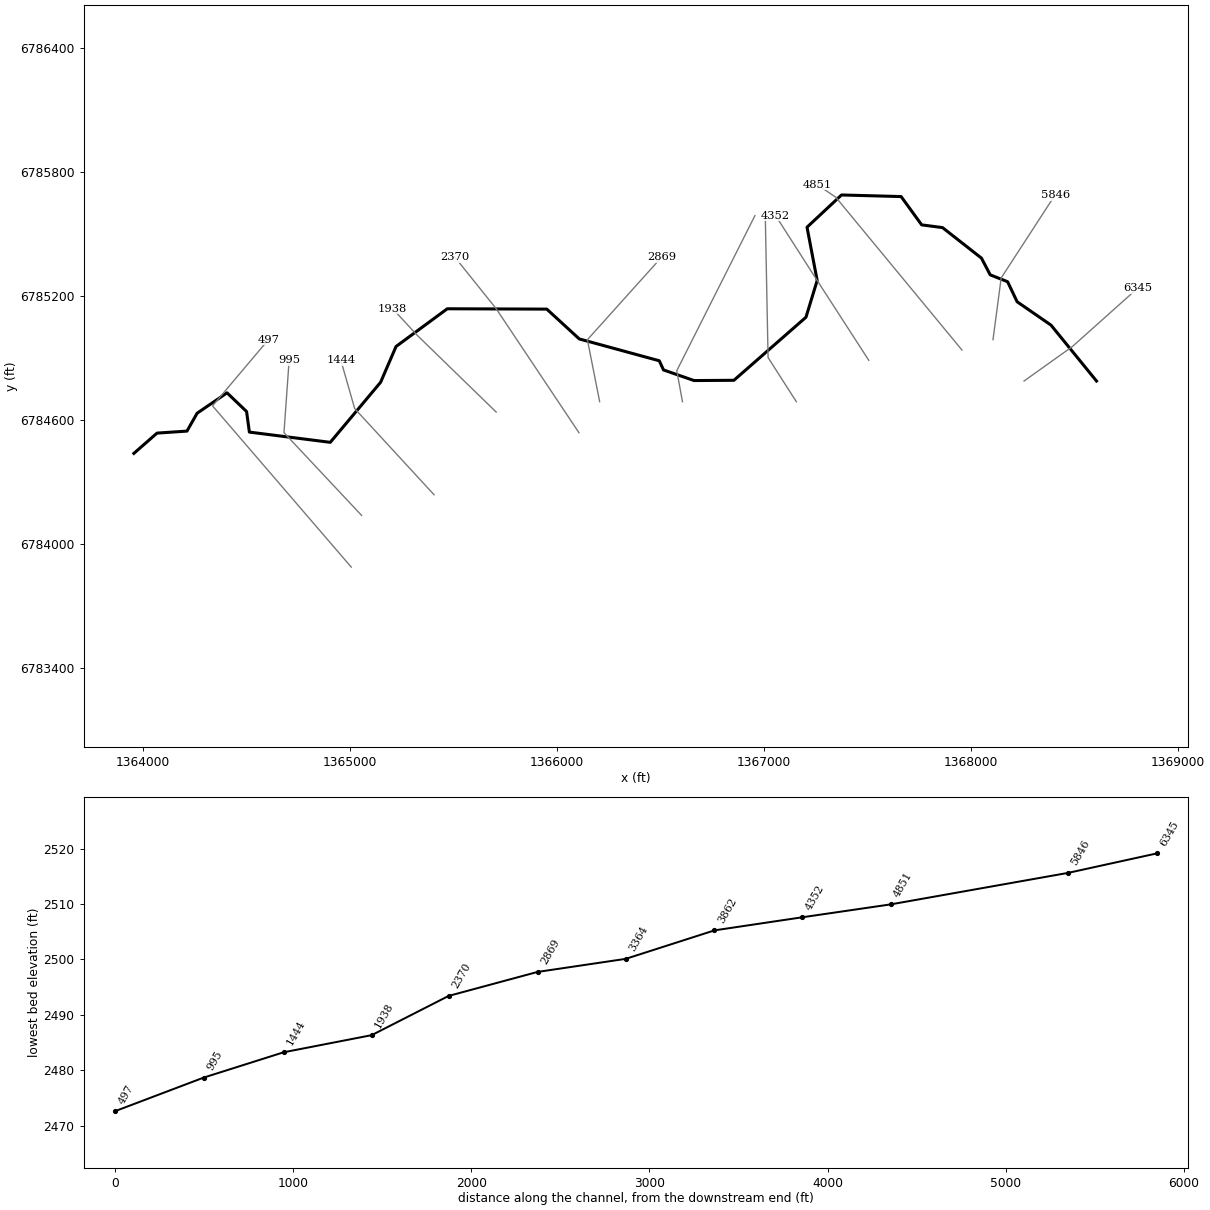
--- Sweetwater Creek Trib 3 T.prj (project) ---

Proj Title=Sweetwater Creek Trib 3 T Base Level Engineering
Current Plan=p01
Default Exp/Contr=0.3,0.1
English Units
Geom File=g01
Flow File=f01
Plan File=p01
BEGIN DESCRIPTION:
Sweetwater Creek Trib 3 T
END DESCRIPTION:

--- Sweetwater Creek Trib 3 T.p01 (plan) ---

Plan Title=Multiple Run
Short Identifier=Multiple
Geom File=g01
Flow File=f01
Subcritical Flow
K Sum by GR= 0
Std Step Tol= 0.01
Critical Tol= 0.01
Num of Std Step Trials= 20
Max Error Tol= 0.3
Flow Tol Ratio= 0.001
Split Flow NTrial= 30
Split Flow Tol= 0.02
Split Flow Ratio= 0.02
Log Output Level= 0
Friction Slope Method= 1
Unsteady Friction Slope Method= 2
Unsteady Bridges Friction Slope Method= 1
Parabolic Critical Depth
Global Vel Dist=  1 , 1 , 1
Global Log Level= 0
CheckData=True
Encroach Param= -1, 0, 0, 0
BEGIN DESCRIPTION:
Multiple Run
END DESCRIPTION:

--- Sweetwater Creek Trib 3 T.f01 (steady flow) ---

Flow Title=Multiple
Number of Profiles=7
Profile Names=10-year,25-year,50-year,1pct_min,100-year,1pct_plu,500-year
River Rch & RM= Sweetwater Creek,Reach-1,6345
     354     503     628     390     778    1552    1208
Boundary for River Rch & Prof#=Sweetwater Creek,Reach-1,1
Up Type=0
Dn Type=3
Dn Slope=0.005
Boundary for River Rch & Prof#=Sweetwater Creek,Reach-1,2
Up Type=0
Dn Type=3
Dn Slope=0.005
Boundary for River Rch & Prof#=Sweetwater Creek,Reach-1,3
Up Type=0
Dn Type=3
Dn Slope=0.005
Boundary for River Rch & Prof#=Sweetwater Creek,Reach-1,4
Up Type=0
Dn Type=3
Dn Slope=0.005
Boundary for River Rch & Prof#=Sweetwater Creek,Reach-1,5
Up Type=0
Dn Type=3
Dn Slope=0.005
Boundary for River Rch & Prof#=Sweetwater Creek,Reach-1,6
Up Type=0
Dn Type=3
Dn Slope=0.005
Boundary for River Rch & Prof#=Sweetwater Creek,Reach-1,7
Up Type=0
Dn Type=3
Dn Slope=0.005

--- Sweetwater Creek Trib 3 T.g01 (geometry) ---

Geom Title=Existing Conditions

River Reach=Sweetwater Creek,Reach-1
Reach XY= 30
      1368605.00      6784788.00      1368385.16      6785058.39
      1368221.64      6785171.30      1368175.46      6785268.37
      1368091.48      6785301.56      1368049.37      6785382.35
      1367861.12      6785530.12      1367760.47      6785543.26
      1367661.21      6785680.20      1367373.22      6785687.91
      1367206.65      6785531.95      1367255.72      6785274.31
      1367201.51      6785096.47      1366853.53      6784791.55
      1366660.93      6784790.26      1366513.50      6784841.55
      1366492.99      6784885.92      1366106.50      6784991.61
      1365949.56      6785135.83      1365468.86      6785137.46
      1365221.49      6784955.05      1365146.86      6784781.94
      1364903.75      6784491.44      1364512.97      6784540.94
      1364499.45      6784640.39      1364405.02      6784730.92
      1364260.64      6784632.35      1364211.45      6784545.74
      1364066.93      6784536.09      1363955.00      6784438.00

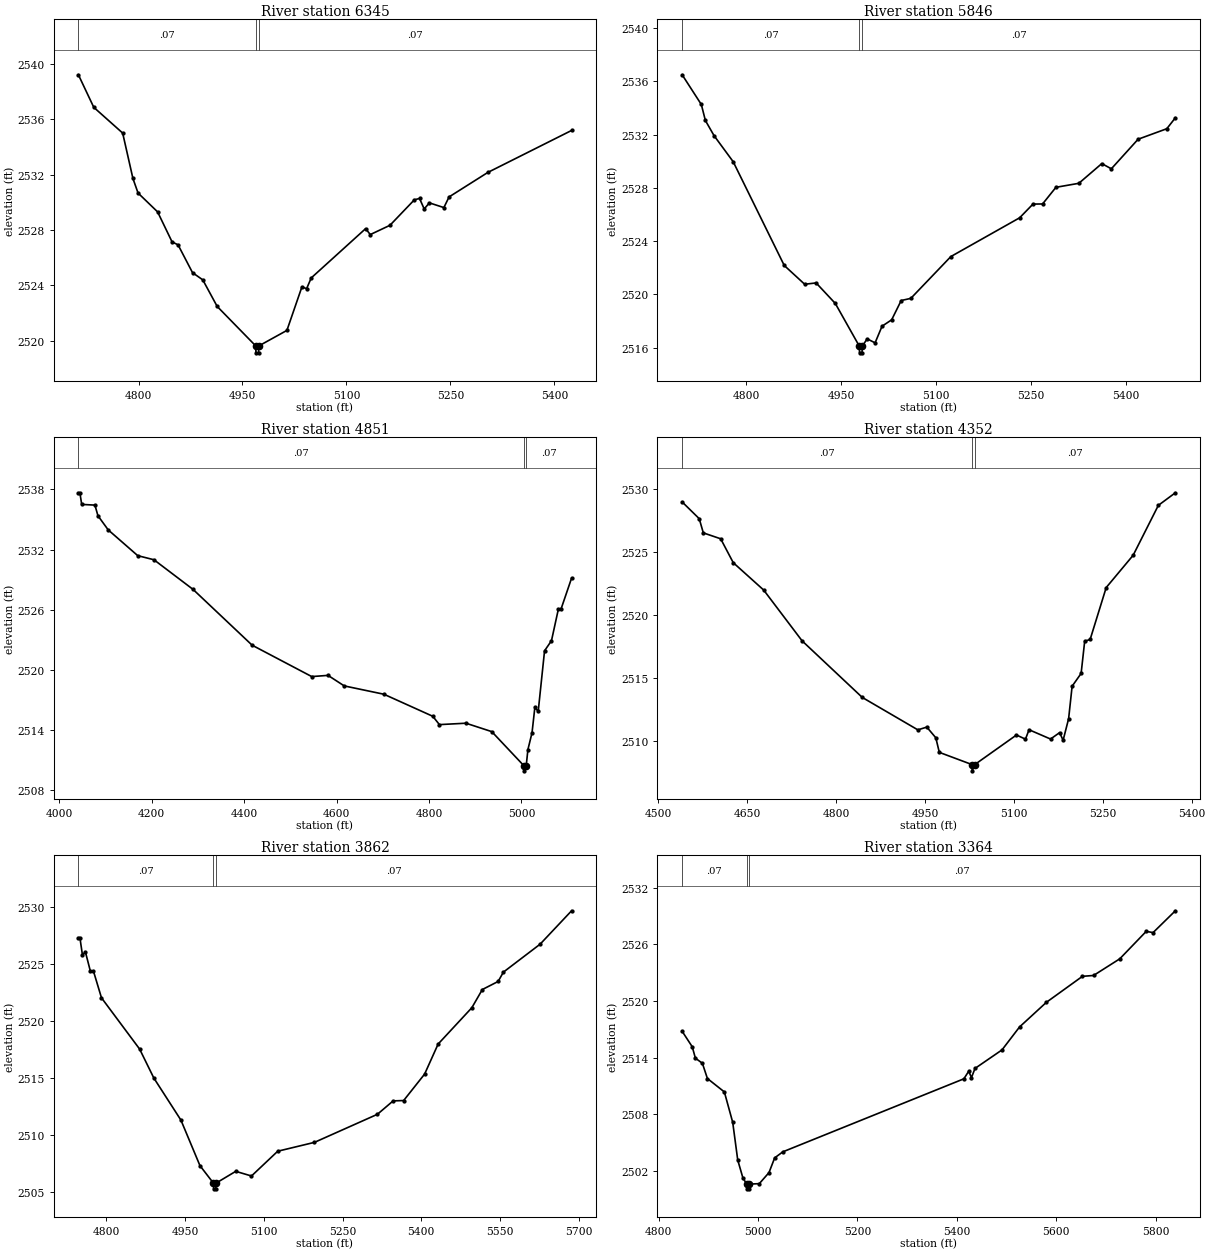
Type RM Length L Ch R = 1,6345,499,499,499
BEGIN DESCRIPTION:
Sweetwater Creek Trib 3 T 11.0
END DESCRIPTION:
XS GIS Cut Line= 3
      1368254.97      6784787.98      1368488.35      6784954.68
      1368805.00      6785238.00
#Sta/Elev= 30
  4713.2 2539.21  4735.4 2536.86  4777.1 2535.00  4791.9 2531.72  4799.3 2530.67
  4827.5 2529.31  4848.4 2527.14  4857.0 2526.93  4877.9 2524.92  4892.7 2524.40
  4913.5 2522.48  4969.1 2519.63  4969.4 2519.13  4973.2 2519.13  4973.6 2519.63
  5014.1 2520.75  5035.8 2523.90  5042.5 2523.76  5049.2 2524.54  5127.7 2528.10
  5134.4 2527.67  5162.8 2528.34  5198.0 2530.18  5205.5 2530.28  5212.2 2529.52
  5219.7 2529.96  5240.6 2529.62  5248.1 2530.39  5304.1 2532.16  5424.9 2535.19
#Mann=3,-1,0
  4713.2    0.07       0  4969.1    0.07       0  4973.6    0.07       0
Bank Sta=4969.1,4973.6
Exp/Cntr=0.3,0.1

Type RM Length L Ch R = 1,5846,995,995,995
BEGIN DESCRIPTION:
Sweetwater Creek Trib 3 T 10.0
END DESCRIPTION:
XS GIS Cut Line= 3
      1368105.00      6784988.00      1368144.47      6785286.50
      1368404.99      6785687.98
#Sta/Elev= 30
  4698.9 2536.49  4729.2 2534.26  4735.6 2533.06  4749.3 2531.92  4779.6 2529.96
  4860.3 2522.17  4892.6 2520.76  4910.7 2520.86  4941.0 2519.32  4979.0 2516.11
  4979.3 2515.61  4983.3 2515.61  4983.6 2516.11  4991.4 2516.66  5003.9 2516.36
  5014.9 2517.61  5030.1 2518.09  5045.2 2519.54  5060.4 2519.70  5123.7 2522.84
  5232.4 2525.75  5253.5 2526.78  5268.7 2526.79  5289.8 2528.04  5326.0 2528.34
  5362.3 2529.82  5377.4 2529.43  5419.7 2531.65  5465.1 2532.44  5478.6 2533.26
#Mann=3,-1,0
  4698.9    0.07       0  4979.0    0.07       0  4983.6    0.07       0
Bank Sta=4979,4983.6
Exp/Cntr=0.3,0.1

Type RM Length L Ch R = 1,4851,499,499,499
BEGIN DESCRIPTION:
Sweetwater Creek Trib 3 T 9.0
END DESCRIPTION:
XS GIS Cut Line= 3
      1367954.99      6784938.01      1367345.20      6785677.52
      1367254.99      6785738.00
#Sta/Elev= 30
  4041.5 2537.66  4044.7 2537.66  4048.7 2536.50  4077.3 2536.43  4083.8 2535.37
  4106.0 2533.96  4169.9 2531.39  4205.0 2530.98  4289.7 2528.02  4417.4 2522.46
  4546.4 2519.33  4581.6 2519.45  4616.7 2518.40  4702.5 2517.57  4808.3 2515.37
  4822.6 2514.54  4880.0 2514.68  4935.9 2513.84  5005.6 2510.43  5006.0 2509.93
  5010.4 2510.43  5014.1 2512.05  5023.0 2513.73  5029.1 2516.25  5036.4 2515.87
  5050.1 2521.90  5065.1 2522.91  5080.1 2526.08  5086.1 2526.11  5108.6 2529.15
#Mann=3,-1,0
  4041.5    0.07       0  5005.6    0.07       0  5010.4    0.07       0
Bank Sta=5005.6,5010.4
Exp/Cntr=0.3,0.1

Type RM Length L Ch R = 1,4352,490,490,490
BEGIN DESCRIPTION:
Sweetwater Creek Trib 3 T 8.0
END DESCRIPTION:
XS GIS Cut Line= 3
      1367505.02      6784887.96      1367255.72      6785274.31
      1367055.01      6785587.99
#Sta/Elev= 30
  4540.2 2528.98  4569.0 2527.65  4575.9 2526.52  4605.2 2526.05  4626.4 2524.15
  4677.8 2521.97  4742.6 2517.93  4844.1 2513.43  4937.9 2510.85  4953.0 2511.07
  4968.2 2510.22  4974.1 2509.06  5029.2 2508.09  5029.6 2507.59  5034.0 2508.09
  5104.3 2510.44  5119.5 2510.11  5125.5 2510.86  5161.8 2510.12  5177.1 2510.63
  5183.0 2510.02  5192.3 2511.74  5198.2 2514.32  5213.4 2515.34  5219.4 2517.90
  5228.6 2518.04  5255.7 2522.17  5301.2 2524.74  5343.7 2528.71  5372.4 2529.71
#Mann=3,-1,0
  4540.2    0.07       0  5029.2    0.07       0  5034.0    0.07       0
Bank Sta=5029.2,5034
Exp/Cntr=0.3,0.1

Type RM Length L Ch R = 1,3862,498,498,498
BEGIN DESCRIPTION:
Sweetwater Creek Trib 3 T 7.0
END DESCRIPTION:
XS GIS Cut Line= 3
      1367154.98      6784688.03      1367018.53      6784901.55
      1367005.00      6785588.02
#Sta/Elev= 30
  4746.6 2527.34  4749.5 2527.34  4754.2 2525.86  4760.1 2526.07  4769.4 2524.40
  4775.3 2524.40  4790.6 2522.05  4863.3 2517.54  4890.4 2514.99  4942.0 2511.29
  4978.3 2507.28  5004.0 2505.74  5004.4 2505.24  5008.6 2505.24  5008.9 2505.74
  5046.5 2506.78  5076.5 2506.37  5126.5 2508.55  5196.5 2509.33  5316.5 2511.80
  5346.5 2512.98  5366.5 2513.01  5406.5 2515.34  5432.2 2517.98  5496.5 2521.18
  5516.5 2522.78  5546.6 2523.49  5556.6 2524.31  5626.6 2526.77  5686.6 2529.71
#Mann=3,-1,0
  4746.6    0.07       0  5004.0    0.07       0  5008.9    0.07       0
Bank Sta=5004,5008.9
Exp/Cntr=0.3,0.1

Type RM Length L Ch R = 1,3364,495,495,495
BEGIN DESCRIPTION:
Sweetwater Creek Trib 3 T 6.0
END DESCRIPTION:
XS GIS Cut Line= 3
      1366605.00      6784687.99      1366577.56      6784838.00
      1366954.99      6785587.98
#Sta/Elev= 30
  4847.5 2516.78  4867.8 2515.14  4874.1 2513.94  4888.2 2513.39  4898.3 2511.78
  4932.4 2510.36  4949.2 2507.14  4959.3 2503.15  4969.5 2501.29  4977.2 2500.60
  4977.5 2500.10  4981.8 2500.10  4982.2 2500.60  5002.7 2500.65  5022.2 2501.82
  5033.6 2503.38  5050.1 2504.02  5414.2 2511.75  5423.9 2512.55  5429.5 2511.88
  5436.6 2512.85  5490.9 2514.81  5526.2 2517.24  5580.2 2519.85  5652.7 2522.60
  5675.0 2522.69  5727.7 2524.45  5781.0 2527.36  5794.8 2527.23  5839.6 2529.54
#Mann=3,-1,0
  4847.5    0.07       0  4977.2    0.07       0  4982.2    0.07       0
Bank Sta=4977.2,4982.2
Exp/Cntr=0.3,0.1

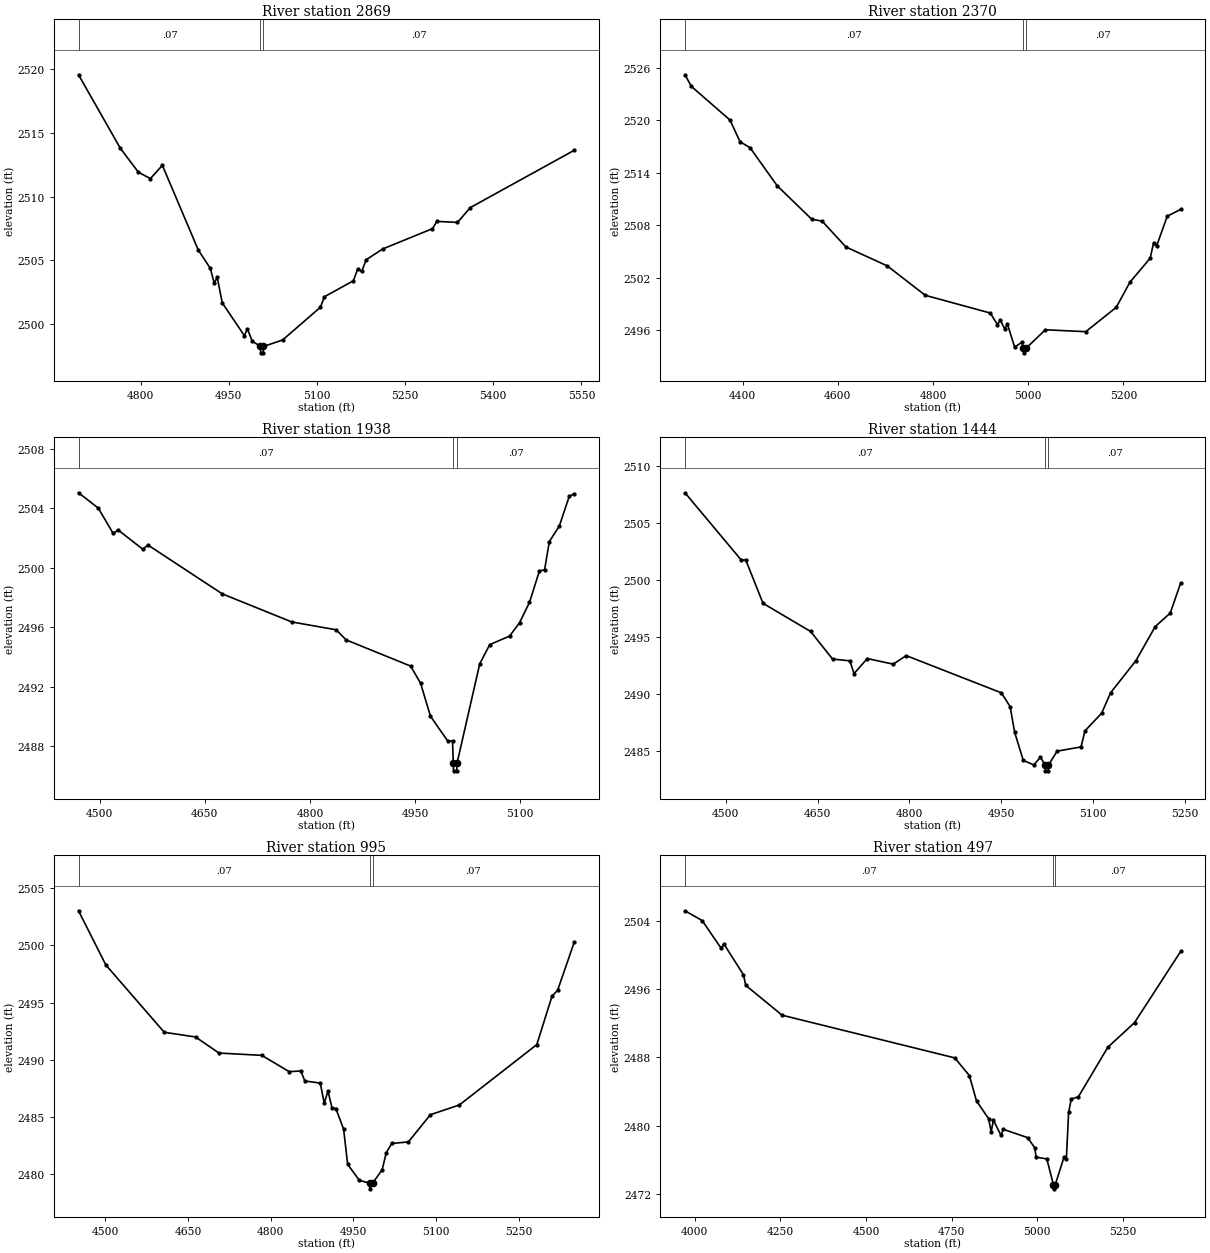
Type RM Length L Ch R = 1,2869,499,499,499
BEGIN DESCRIPTION:
Sweetwater Creek Trib 3 T 5.0
END DESCRIPTION:
XS GIS Cut Line= 3
      1366205.00      6784688.01      1366145.84      6784987.83
      1366505.00      6785387.99
#Sta/Elev= 30
  4694.4 2519.57  4765.7 2513.79  4796.3 2511.92  4816.7 2511.42  4837.1 2512.46
  4898.2 2505.81  4918.6 2504.38  4925.3 2503.21  4930.4 2503.67  4939.0 2501.66
  4976.6 2499.09  4981.7 2499.62  4990.0 2498.66  5004.0 2498.24  5004.4 2497.74
  5008.7 2497.74  5009.1 2498.24  5041.7 2498.75  5106.0 2501.32  5112.7 2502.14
  5162.1 2503.40  5169.5 2504.34  5176.3 2504.13  5183.8 2505.05  5212.2 2505.90
  5296.6 2507.49  5304.1 2508.06  5339.2 2507.98  5360.9 2509.14  5537.7 2513.64
#Mann=3,-1,0
  4694.4    0.07       0  5004.0    0.07       0  5009.1    0.07       0
Bank Sta=5004,5009.1
Exp/Cntr=0.3,0.1

Type RM Length L Ch R = 1,2370,432,432,432
BEGIN DESCRIPTION:
Sweetwater Creek Trib 3 T 4.0
END DESCRIPTION:
XS GIS Cut Line= 3
      1366104.99      6784538.01      1365705.00      6785138.00
      1365504.97      6785388.03
#Sta/Elev= 30
  4278.9 2525.21  4292.4 2523.88  4373.5 2520.03  4394.6 2517.55  4415.6 2516.87
  4472.7 2512.51  4544.8 2508.71  4567.3 2508.46  4616.9 2505.52  4704.0 2503.35
  4783.7 2499.99  4920.4 2497.96  4935.4 2496.63  4941.4 2497.17  4950.4 2496.15
  4956.4 2496.67  4971.5 2494.06  4986.5 2494.61  4989.9 2493.91  4990.3 2493.41
  4995.1 2493.91  5036.0 2496.05  5120.9 2495.83  5184.9 2498.61  5213.7 2501.49
  5256.1 2504.22  5263.3 2505.95  5269.7 2505.62  5292.1 2509.04  5320.2 2509.81
#Mann=3,-1,0
  4278.9    0.07       0  4989.9    0.07       0  4995.1    0.07       0
Bank Sta=4989.9,4995.1
Exp/Cntr=0.3,0.1

Type RM Length L Ch R = 1,1938,494,494,494
BEGIN DESCRIPTION:
Sweetwater Creek Trib 3 T 3.0
END DESCRIPTION:
XS GIS Cut Line= 3
      1365705.02      6784637.99      1365325.08      6785007.80
      1365205.01      6785137.98
#Sta/Elev= 30
  4469.8 2505.04  4498.0 2504.01  4519.3 2502.30  4526.3 2502.54  4561.8 2501.23
  4568.7 2501.53  4674.9 2498.24  4774.0 2496.35  4837.5 2495.82  4851.7 2495.14
  4943.7 2493.38  4957.9 2492.23  4972.0 2490.01  4996.6 2488.34  5003.5 2488.34
  5004.6 2486.83  5005.0 2486.33  5009.5 2486.33  5009.9 2486.83  5042.4 2493.54
  5056.6 2494.82  5085.0 2495.40  5099.1 2496.29  5113.3 2497.66  5127.5 2499.78
  5134.9 2499.86  5141.7 2501.76  5155.9 2502.80  5170.0 2504.79  5177.1 2504.98
#Mann=3,-1,0
  4469.8    0.07       0  5004.6    0.07       0  5009.9    0.07       0
Bank Sta=5004.6,5009.9
Exp/Cntr=0.3,0.1

Type RM Length L Ch R = 1,1444,449,449,449
BEGIN DESCRIPTION:
Sweetwater Creek Trib 3 T 2.0
END DESCRIPTION:
XS GIS Cut Line= 3
      1365405.03      6784237.97      1365021.58      6784654.70
      1364955.00      6784887.99
#Sta/Elev= 30
  4433.7 2507.66  4525.9 2501.73  4532.7 2501.78  4561.1 2497.95  4638.7 2495.48
  4674.5 2493.06  4702.8 2492.90  4709.6 2491.78  4731.2 2493.10  4773.5 2492.61
  4794.7 2493.36  4950.1 2490.09  4964.3 2488.88  4971.7 2486.63  4985.8 2484.16
  5002.9 2483.76  5013.8 2484.43  5021.6 2483.74  5022.0 2483.24  5026.5 2483.24
  5026.9 2483.74  5041.0 2484.97  5080.0 2485.34  5086.6 2486.76  5113.8 2488.31
  5128.2 2490.09  5169.8 2492.93  5201.0 2495.90  5225.7 2497.10  5242.6 2499.73
#Mann=3,-1,0
  4433.7    0.07       0  5021.6    0.07       0  5026.9    0.07       0
Bank Sta=5021.6,5026.9
Exp/Cntr=0.3,0.1

Type RM Length L Ch R = 1,995,498,498,498
BEGIN DESCRIPTION:
Sweetwater Creek Trib 3 T 1.0
END DESCRIPTION:
XS GIS Cut Line= 3
      1365055.01      6784137.99      1364680.08      6784538.20
      1364705.00      6784888.01
#Sta/Elev= 30
  4451.6 2503.04  4501.2 2498.29  4607.2 2492.39  4663.9 2491.98  4706.4 2490.57
  4784.0 2490.37  4833.8 2488.94  4854.8 2489.00  4862.2 2488.12  4890.1 2487.94
  4897.3 2486.19  4904.2 2487.24  4911.5 2485.74  4918.4 2485.71  4932.5 2483.90
  4939.8 2480.82  4960.9 2479.42  4979.6 2479.17  4980.0 2478.67  4985.1 2479.17
  5002.4 2480.34  5009.8 2481.83  5019.9 2482.65  5049.9 2482.78  5090.0 2485.17
  5142.4 2486.02  5282.9 2491.31  5310.6 2495.57  5320.6 2496.06  5350.7 2500.27
#Mann=3,-1,0
  4451.6    0.07       0  4979.6    0.07       0  4985.1    0.07       0
Bank Sta=4979.6,4985.1
Exp/Cntr=0.3,0.1

Type RM Length L Ch R = 1,497,0,0,0
BEGIN DESCRIPTION:
Sweetwater Creek Trib 3 T 2507
END DESCRIPTION:
XS GIS Cut Line= 3
      1365005.02      6783887.98      1364335.06      6784667.82
      1364605.01      6784988.01
#Sta/Elev= 30
  3971.9 2505.19  4021.9 2504.05  4077.8 2500.78  4085.5 2501.30  4142.6 2497.69
  4149.2 2496.45  4255.6 2492.95  4759.3 2487.95  4802.1 2485.88  4822.9 2482.90
  4858.1 2480.83  4865.7 2479.29  4872.3 2480.65  4894.3 2478.87  4900.9 2479.58
  4972.2 2478.60  4993.0 2477.41  4996.8 2476.31  5028.1 2476.11  5047.4 2473.10
  5047.8 2472.60  5052.9 2473.10  5078.7 2476.36  5085.2 2476.10  5091.8 2481.55
  5099.5 2483.12  5120.4 2483.39  5206.2 2489.19  5284.2 2492.08  5418.8 2500.42
#Mann=3,-1,0
  3971.9    0.07       0  5047.4    0.07       0  5052.9    0.07       0
Bank Sta=5047.4,5052.9
Exp/Cntr=0.3,0.1

Chan Stop Cuts=-1