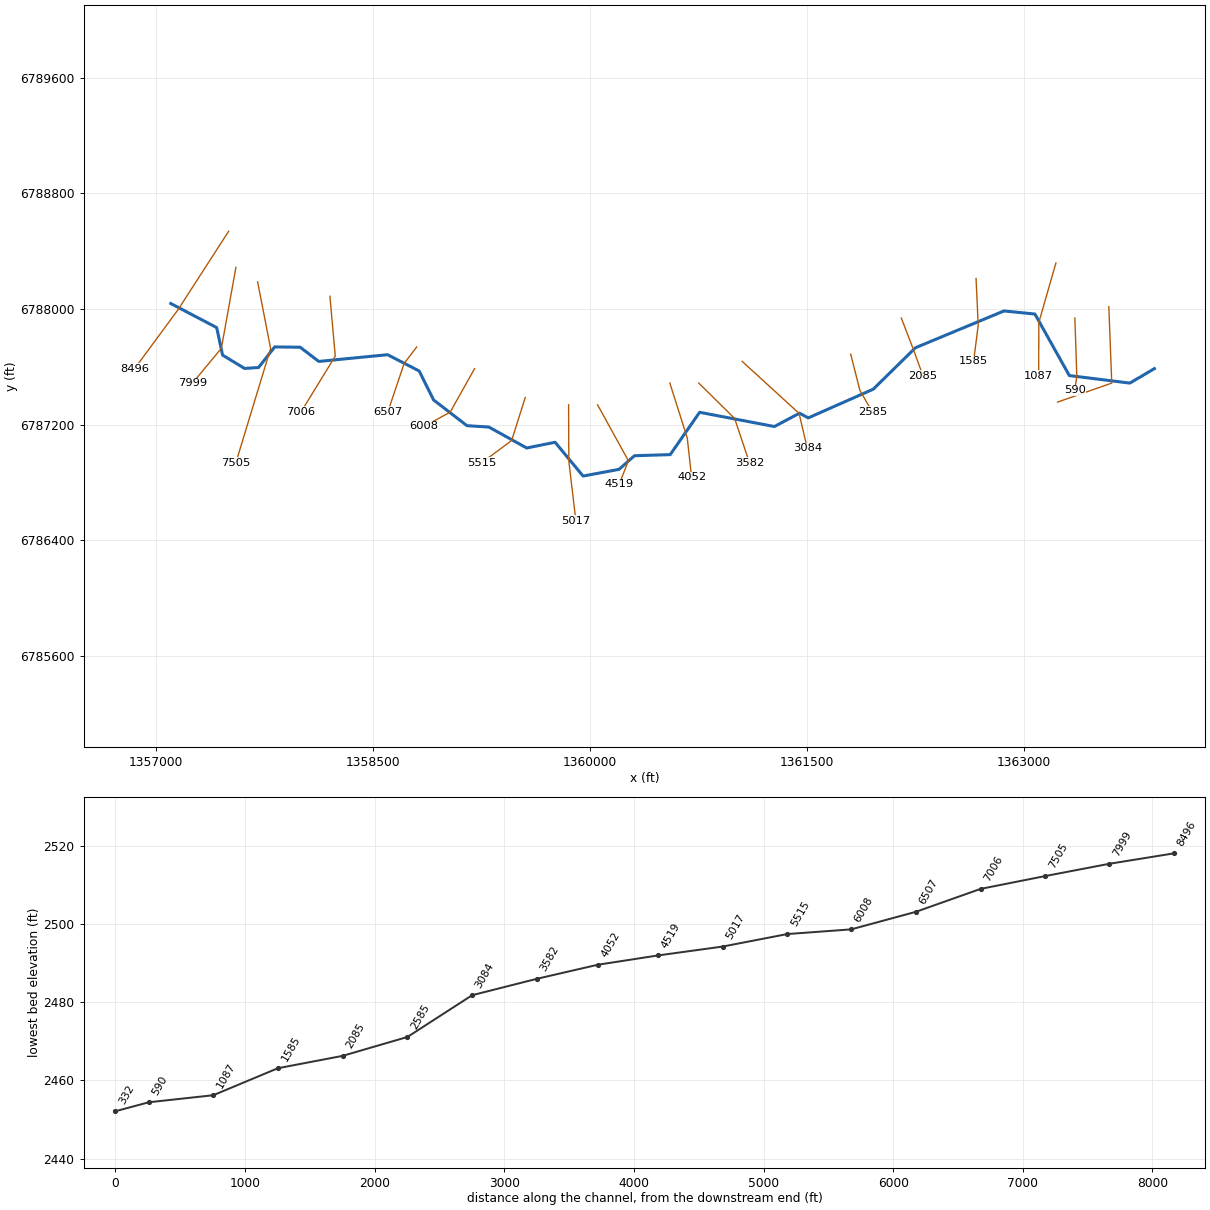
--- Sweetwater Creek Trib 4.prj (project) ---

Proj Title=Sweetwater Creek Trib 4 Base Level Engineering
Current Plan=p01
Default Exp/Contr=0.3,0.1
English Units
Geom File=g01
Flow File=f01
Plan File=p01
BEGIN DESCRIPTION:
Sweetwater Creek Trib 4
END DESCRIPTION:

--- Sweetwater Creek Trib 4.p01 (plan) ---

Plan Title=Multiple Run
Short Identifier=Multiple
Geom File=g01
Flow File=f01
Subcritical Flow
K Sum by GR= 0
Std Step Tol= 0.01
Critical Tol= 0.01
Num of Std Step Trials= 20
Max Error Tol= 0.3
Flow Tol Ratio= 0.001
Split Flow NTrial= 30
Split Flow Tol= 0.02
Split Flow Ratio= 0.02
Log Output Level= 0
Friction Slope Method= 1
Unsteady Friction Slope Method= 2
Unsteady Bridges Friction Slope Method= 1
Parabolic Critical Depth
Global Vel Dist=  1 , 1 , 1
Global Log Level= 0
CheckData=True
Encroach Param= -1, 0, 0, 0
BEGIN DESCRIPTION:
Multiple Run
END DESCRIPTION:

--- Sweetwater Creek Trib 4.f01 (steady flow) ---

Flow Title=Multiple
Number of Profiles=7
Profile Names=10-year,25-year,50-year,1pct_min,100-year,1pct_plu,500-year
River Rch & RM= Sweetwater Creek,Reach-1,8496
     375     539     678     424     846    1689    1335
River Rch & RM= Sweetwater Creek,Reach-1,2585
     483     705     896     566    1129    2253    1817
Boundary for River Rch & Prof#=Sweetwater Creek,Reach-1,1
Up Type=0
Dn Type=3
Dn Slope=0.005
Boundary for River Rch & Prof#=Sweetwater Creek,Reach-1,2
Up Type=0
Dn Type=3
Dn Slope=0.005
Boundary for River Rch & Prof#=Sweetwater Creek,Reach-1,3
Up Type=0
Dn Type=3
Dn Slope=0.005
Boundary for River Rch & Prof#=Sweetwater Creek,Reach-1,4
Up Type=0
Dn Type=3
Dn Slope=0.005
Boundary for River Rch & Prof#=Sweetwater Creek,Reach-1,5
Up Type=0
Dn Type=3
Dn Slope=0.005
Boundary for River Rch & Prof#=Sweetwater Creek,Reach-1,6
Up Type=0
Dn Type=3
Dn Slope=0.005
Boundary for River Rch & Prof#=Sweetwater Creek,Reach-1,7
Up Type=0
Dn Type=3
Dn Slope=0.005

--- Sweetwater Creek Trib 4.g01 (geometry) ---

Geom Title=Existing Conditions

River Reach=Sweetwater Creek,Reach-1
Reach XY= 30
      1357105.00      6788038.00      1357422.14      6787871.54
      1357462.70      6787681.52      1357614.70      6787589.24
      1357711.45      6787595.64      1357823.11      6787737.96
      1357999.55      6787735.82      1358127.72      6787637.62
      1358603.45      6787684.25      1358822.05      6787571.51
      1358921.63      6787371.29      1359152.56      6787193.48
      1359303.44      6787184.24      1359565.50      6787039.19
      1359761.76      6787078.88      1359954.89      6786845.31
      1360203.53      6786891.55      1360310.45      6786985.82
      1360557.45      6786993.46      1360760.65      6787286.03
      1361277.77      6787187.71      1361451.67      6787279.98
      1361511.66      6787247.32      1361961.17      6787445.88
      1362252.70      6787732.17      1362864.65      6787986.64
      1363078.90      6787965.30      1363316.87      6787539.74
      1363735.02      6787487.96      1363905.00      6787588.00

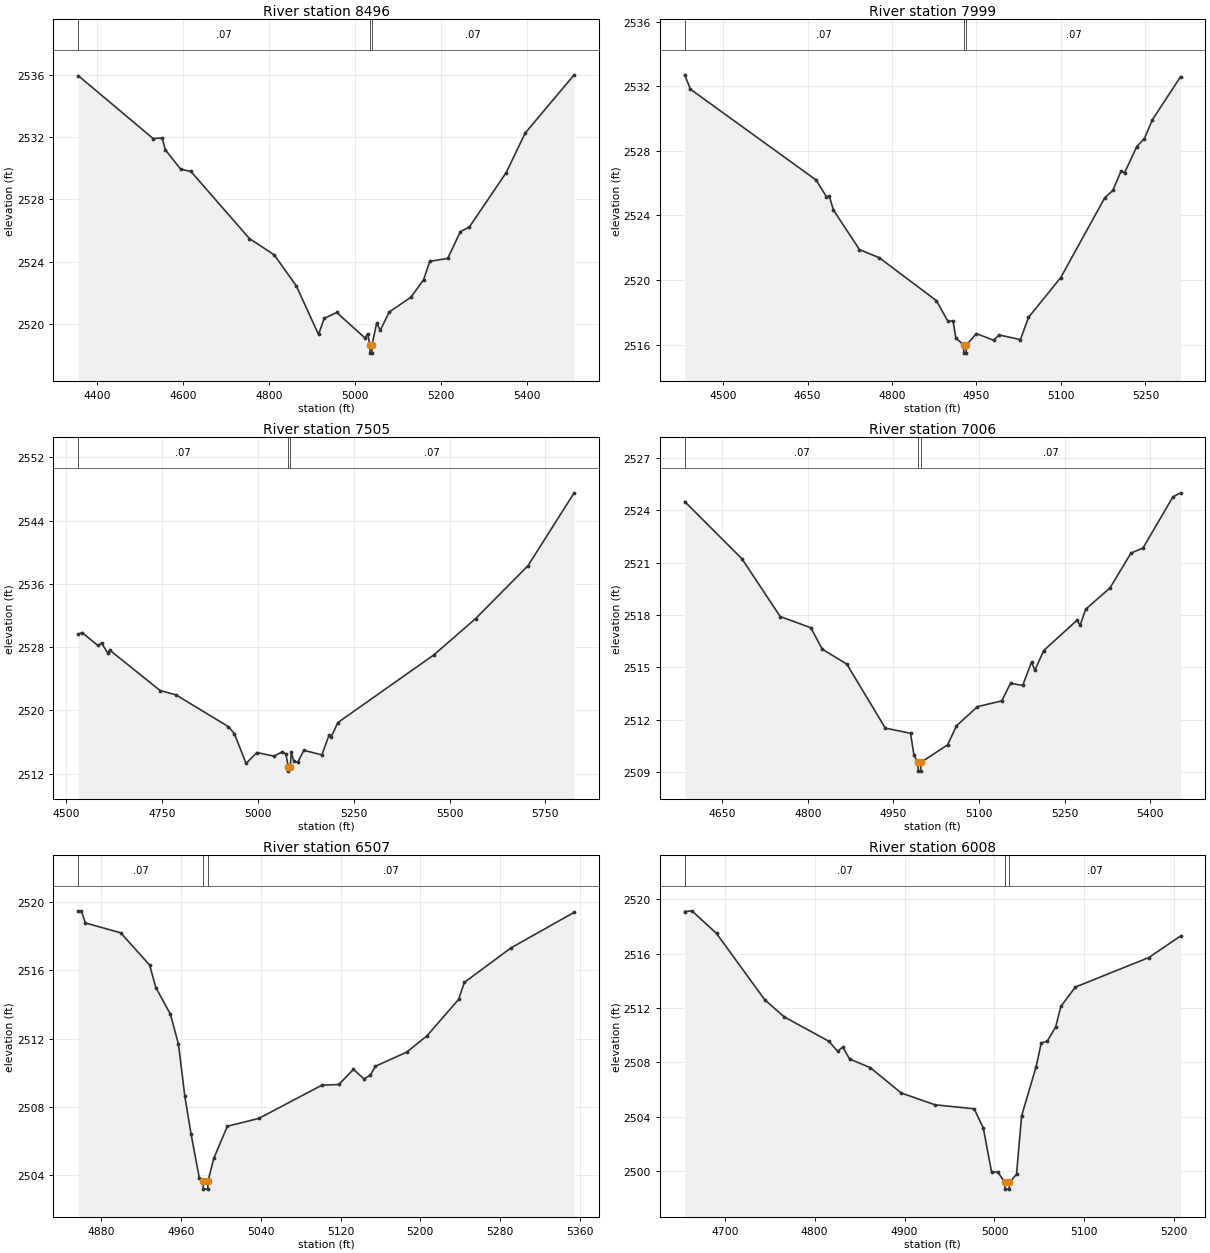
Type RM Length L Ch R = 1,8496,497,497,497
BEGIN DESCRIPTION:
Sweetwater Creek Trib 4 16.0
END DESCRIPTION:
XS GIS Cut Line= 3
      1357504.99      6788537.98      1357156.43      6787997.54
      1356855.00      6787588.00
#Sta/Elev= 30
  4356.9 2535.94  4530.8 2531.90  4551.9 2531.94  4559.2 2531.18  4594.9 2529.93
  4618.6 2529.79  4754.5 2525.48  4812.0 2524.44  4863.4 2522.44  4914.9 2519.33
  4928.1 2520.36  4957.2 2520.74  5022.9 2519.10  5029.1 2519.38  5034.3 2518.63
  5034.7 2518.13  5038.7 2518.13  5039.0 2518.63  5049.9 2520.05  5058.4 2519.60
  5079.2 2520.77  5129.4 2521.72  5158.7 2522.83  5173.3 2524.02  5215.0 2524.21
  5244.3 2525.93  5265.1 2526.22  5350.8 2529.72  5394.7 2532.25  5508.5 2535.99
#Mann=3,-1,0
  4356.9    0.07       0  5034.3    0.07       0  5039.0    0.07       0
Bank Sta=5034.3,5039
Exp/Cntr=0.3,0.1

Type RM Length L Ch R = 1,7999,494,494,494
BEGIN DESCRIPTION:
Sweetwater Creek Trib 4 15.0
END DESCRIPTION:
XS GIS Cut Line= 3
      1357555.01      6788288.03      1357454.54      6787728.68
      1357255.03      6787488.03
#Sta/Elev= 30
  4431.7 2532.70  4441.9 2531.81  4665.4 2526.18  4683.5 2525.15  4688.5 2525.20
  4695.9 2524.33  4742.2 2521.88  4777.2 2521.38  4878.8 2518.72  4899.1 2517.45
  4908.4 2517.46  4913.4 2516.41  4927.2 2515.97  4927.5 2515.47  4931.6 2515.47
  4932.0 2515.97  4949.9 2516.68  4980.4 2516.27  4990.5 2516.59  5028.1 2516.31
  5042.4 2517.68  5099.7 2520.15  5177.9 2525.09  5192.2 2525.54  5206.5 2526.72
  5213.0 2526.63  5234.7 2528.26  5248.2 2528.75  5262.5 2529.92  5312.6 2532.59
#Mann=3,-1,0
  4431.7    0.07       0  4927.2    0.07       0  4932.0    0.07       0
Bank Sta=4927.2,4932
Exp/Cntr=0.3,0.1

Type RM Length L Ch R = 1,7505,499,499,499
BEGIN DESCRIPTION:
Sweetwater Creek Trib 4 14.0
END DESCRIPTION:
XS GIS Cut Line= 3
      1357705.01      6788187.96      1357794.88      6787727.65
      1357555.00      6786937.99
#Sta/Elev= 30
  4531.0 2529.62  4541.2 2529.84  4581.9 2528.22  4592.1 2528.50  4608.3 2527.23
  4613.4 2527.62  4744.9 2522.51  4785.7 2521.98  4922.8 2517.96  4938.5 2517.07
  4969.1 2513.30  4997.3 2514.68  5041.4 2514.23  5062.3 2514.73  5072.8 2514.54
  5079.4 2512.83  5079.7 2512.33  5084.3 2512.83  5087.0 2514.77  5093.7 2513.55
  5104.2 2513.48  5119.9 2514.96  5166.9 2514.38  5185.7 2516.89  5190.9 2516.64
  5208.7 2518.47  5459.2 2527.02  5568.2 2531.61  5705.0 2538.30  5825.3 2547.50
#Mann=3,-1,0
  4531.0    0.07       0  5079.4    0.07       0  5084.3    0.07       0
Bank Sta=5079.4,5084.3
Exp/Cntr=0.3,0.1

Type RM Length L Ch R = 1,7006,499,499,499
BEGIN DESCRIPTION:
Sweetwater Creek Trib 4 13.0
END DESCRIPTION:
XS GIS Cut Line= 3
      1358205.00      6788087.96      1358241.85      6787674.20
      1358005.02      6787288.04
#Sta/Elev= 30
  4584.6 2524.51  4685.0 2521.22  4751.9 2517.91  4805.4 2517.27  4825.5 2516.04
  4868.5 2515.18  4935.9 2511.51  4980.1 2511.21  4986.1 2509.95  4993.1 2509.54
  4993.4 2509.04  4997.7 2509.04  4998.1 2509.54  5045.1 2510.55  5060.5 2511.64
  5097.2 2512.74  5139.8 2513.07  5155.2 2514.08  5176.5 2513.96  5192.0 2515.30
  5197.8 2514.83  5213.3 2515.96  5271.3 2517.69  5277.1 2517.42  5286.7 2518.33
  5329.3 2519.55  5366.0 2521.55  5387.3 2521.85  5439.5 2524.78  5453.0 2525.01
#Mann=3,-1,0
  4584.6    0.07       0  4993.1    0.07       0  4998.1    0.07       0
Bank Sta=4993.1,4998.1
Exp/Cntr=0.3,0.1

Type RM Length L Ch R = 1,6507,499,499,499
BEGIN DESCRIPTION:
Sweetwater Creek Trib 4 12.0
END DESCRIPTION:
XS GIS Cut Line= 3
      1358804.98      6787737.97      1358718.07      6787624.03
      1358605.01      6787288.04
#Sta/Elev= 30
  4856.7 2519.50  4859.8 2519.50  4863.9 2518.79  4899.3 2518.21  4928.4 2516.32
  4934.6 2515.00  4949.2 2513.44  4957.3 2511.68  4963.7 2508.63  4970.0 2506.39
  4978.2 2503.85  4981.9 2503.67  4982.3 2503.17  4986.7 2503.17  4987.1 2503.67
  4992.8 2504.98  5006.4 2506.86  5038.0 2507.32  5101.3 2509.27  5118.3 2509.31
  5133.0 2510.20  5143.5 2509.64  5149.8 2509.85  5155.0 2510.38  5186.5 2511.21
  5206.8 2512.17  5238.5 2514.30  5244.3 2515.30  5291.2 2517.33  5354.5 2519.41
#Mann=3,-1,0
  4856.7    0.07       0  4981.9    0.07       0  4987.1    0.07       0
Bank Sta=4981.9,4987.1
Exp/Cntr=0.3,0.1

Type RM Length L Ch R = 1,6008,493,493,493
BEGIN DESCRIPTION:
Sweetwater Creek Trib 4 11.0
END DESCRIPTION:
XS GIS Cut Line= 3
      1359204.99      6787587.98      1359036.59      6787287.44
      1358855.03      6787188.02
#Sta/Elev= 30
  4655.5 2519.10  4663.5 2519.15  4690.9 2517.49  4744.5 2512.61  4766.2 2511.35
  4816.0 2509.55  4825.5 2508.82  4831.3 2509.13  4838.9 2508.25  4861.8 2507.62
  4896.3 2505.75  4934.0 2504.88  4977.4 2504.59  4987.6 2503.17  4996.8 2499.93
  5003.8 2499.93  5011.4 2499.18  5011.8 2498.68  5016.3 2498.68  5016.7 2499.18
  5024.5 2499.77  5030.2 2504.07  5046.3 2507.68  5052.0 2509.43  5058.8 2509.57
  5068.1 2510.62  5073.8 2512.12  5089.9 2513.54  5171.5 2515.71  5207.0 2517.30
#Mann=3,-1,0
  4655.5    0.07       0  5011.4    0.07       0  5016.7    0.07       0
Bank Sta=5011.4,5016.7
Exp/Cntr=0.3,0.1

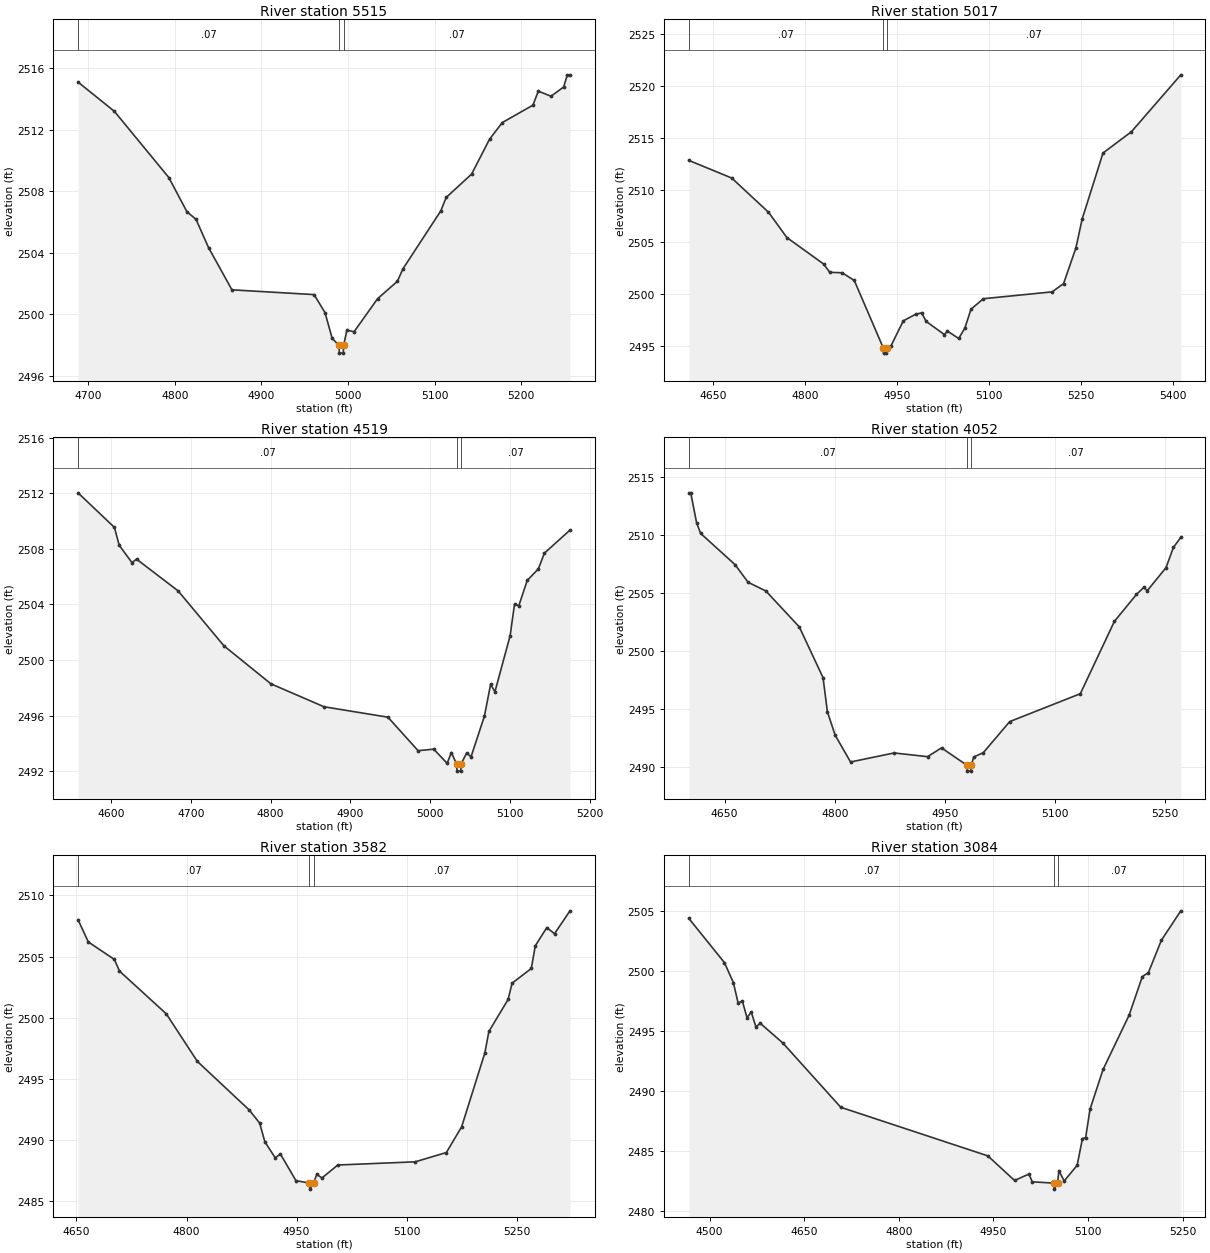
Type RM Length L Ch R = 1,5515,498,498,498
BEGIN DESCRIPTION:
Sweetwater Creek Trib 4 10.0
END DESCRIPTION:
XS GIS Cut Line= 3
      1359555.00      6787388.00      1359461.11      6787090.68
      1359255.00      6786938.00
#Sta/Elev= 30
  4688.2 2515.08  4730.2 2513.18  4793.1 2508.88  4814.0 2506.66  4824.5 2506.17
  4839.0 2504.33  4866.0 2501.59  4960.9 2501.28  4973.5 2500.11  4981.8 2498.44
  4989.6 2497.98  4990.1 2497.48  4994.6 2497.48  4995.0 2497.98  4998.8 2498.97
  5007.1 2498.87  5034.2 2501.01  5057.2 2502.15  5063.4 2502.94  5107.2 2506.71
  5113.5 2507.59  5142.8 2509.10  5163.6 2511.37  5178.3 2512.45  5213.7 2513.58
  5219.9 2514.49  5234.6 2514.16  5249.2 2514.76  5253.4 2515.55  5256.5 2515.55
#Mann=3,-1,0
  4688.2    0.07       0  4989.6    0.07       0  4995.0    0.07       0
Bank Sta=4989.6,4995
Exp/Cntr=0.3,0.1

Type RM Length L Ch R = 1,5017,498,498,498
BEGIN DESCRIPTION:
Sweetwater Creek Trib 4 9.0
END DESCRIPTION:
XS GIS Cut Line= 3
      1359855.00      6787338.03      1359856.55      6786948.63
      1359905.00      6786537.98
#Sta/Elev= 30
  4610.6 2512.84  4680.6 2511.14  4740.6 2507.85  4770.6 2505.41  4830.6 2502.86
  4840.6 2502.06  4860.6 2502.02  4880.6 2501.28  4927.9 2494.78  4928.3 2494.28
  4932.9 2494.28  4933.4 2494.78  4940.6 2494.99  4960.6 2497.39  4980.6 2498.02
  4990.6 2498.16  4997.8 2497.34  5027.6 2496.07  5032.7 2496.40  5051.0 2495.69
  5061.1 2496.70  5071.1 2498.51  5091.3 2499.52  5203.6 2500.18  5222.2 2500.98
  5242.3 2504.41  5252.4 2507.17  5286.5 2513.55  5332.9 2515.60  5413.5 2521.08
#Mann=3,-1,0
  4610.6    0.07       0  4927.9    0.07       0  4933.4    0.07       0
Bank Sta=4927.9,4933.4
Exp/Cntr=0.3,0.1

Type RM Length L Ch R = 1,4519,467,467,467
BEGIN DESCRIPTION:
Sweetwater Creek Trib 4 8.0
END DESCRIPTION:
XS GIS Cut Line= 3
      1360054.99      6787338.01      1360268.21      6786951.64
      1360205.01      6786788.02
#Sta/Elev= 30
  4558.7 2512.03  4604.4 2509.54  4610.3 2508.26  4626.3 2507.01  4632.1 2507.26
  4684.3 2504.97  4741.5 2501.03  4800.5 2498.29  4867.1 2496.64  4947.2 2495.89
  4985.0 2493.48  5004.6 2493.59  5021.4 2492.57  5026.7 2493.35  5033.3 2492.51
  5033.8 2492.01  5038.4 2492.01  5038.8 2492.51  5046.0 2493.33  5051.3 2493.03
  5068.2 2495.98  5075.9 2498.26  5081.3 2497.72  5100.4 2501.76  5105.9 2504.04
  5111.2 2503.90  5121.8 2505.73  5135.8 2506.56  5143.3 2507.69  5175.4 2509.35
#Mann=3,-1,0
  4558.7    0.07       0  5033.3    0.07       0  5038.8    0.07       0
Bank Sta=5033.3,5038.8
Exp/Cntr=0.3,0.1

Type RM Length L Ch R = 1,4052,470,470,470
BEGIN DESCRIPTION:
Sweetwater Creek Trib 4 7.0
END DESCRIPTION:
XS GIS Cut Line= 3
      1360555.01      6787487.97      1360675.48      6787107.80
      1360705.00      6786838.01
#Sta/Elev= 30
  4601.2 2513.66  4603.8 2513.66  4611.7 2511.09  4617.3 2510.15  4664.1 2507.46
  4681.9 2505.93  4706.1 2505.18  4751.7 2502.07  4784.0 2497.69  4790.0 2494.73
  4800.5 2492.72  4821.5 2490.40  4880.8 2491.18  4926.4 2490.86  4945.4 2491.62
  4980.2 2490.11  4980.6 2489.61  4985.3 2489.61  4985.8 2490.11  4989.3 2490.83
  5002.4 2491.21  5038.3 2493.89  5134.5 2496.30  5180.9 2502.55  5211.0 2504.88
  5220.8 2505.48  5225.8 2505.21  5251.3 2507.20  5261.3 2508.94  5271.4 2509.82
#Mann=3,-1,0
  4601.2    0.07       0  4980.2    0.07       0  4985.8    0.07       0
Bank Sta=4980.2,4985.8
Exp/Cntr=0.3,0.1

Type RM Length L Ch R = 1,3582,498,498,498
BEGIN DESCRIPTION:
Sweetwater Creek Trib 4 6.0
END DESCRIPTION:
XS GIS Cut Line= 3
      1360755.03      6787487.97      1361002.67      6787243.75
      1361104.99      6786938.02
#Sta/Elev= 30
  4652.2 2508.02  4666.2 2506.20  4701.7 2504.77  4708.7 2503.82  4772.4 2500.33
  4814.8 2496.44  4885.5 2492.47  4899.7 2491.40  4906.7 2489.88  4920.8 2488.57
  4927.9 2488.88  4949.1 2486.70  4967.5 2486.51  4968.0 2486.01  4973.2 2486.51
  4977.4 2487.22  4984.5 2486.92  5006.1 2487.98  5111.5 2488.24  5154.0 2489.00
  5174.8 2491.10  5206.4 2497.13  5211.9 2498.89  5238.1 2501.50  5243.5 2502.83
  5269.7 2504.03  5275.1 2505.88  5290.8 2507.37  5301.3 2506.87  5322.4 2508.74
#Mann=3,-1,0
  4652.2    0.07       0  4967.5    0.07       0  4973.2    0.07       0
Bank Sta=4967.5,4973.2
Exp/Cntr=0.3,0.1

Type RM Length L Ch R = 1,3084,499,499,499
BEGIN DESCRIPTION:
Sweetwater Creek Trib 4 5.0
END DESCRIPTION:
XS GIS Cut Line= 3
      1361054.97      6787638.03      1361448.34      6787278.68
      1361505.01      6787037.96
#Sta/Elev= 30
  4467.2 2504.38  4523.7 2500.69  4537.9 2499.02  4545.3 2497.33  4552.0 2497.50
  4559.4 2496.11  4566.2 2496.57  4573.6 2495.34  4580.4 2495.64  4616.2 2494.00
  4708.1 2488.64  4941.3 2484.59  4983.7 2482.54  5006.5 2483.08  5011.7 2482.43
  5046.0 2482.32  5046.5 2481.82  5051.8 2482.32  5054.0 2483.36  5062.3 2482.50
  5082.9 2483.80  5091.3 2486.03  5096.4 2486.12  5103.4 2488.49  5124.0 2491.79
  5165.1 2496.29  5186.3 2499.53  5195.9 2499.86  5216.4 2502.55  5247.3 2505.01
#Mann=3,-1,0
  4467.2    0.07       0  5046.0    0.07       0  5051.8    0.07       0
Bank Sta=5046,5051.8
Exp/Cntr=0.3,0.1

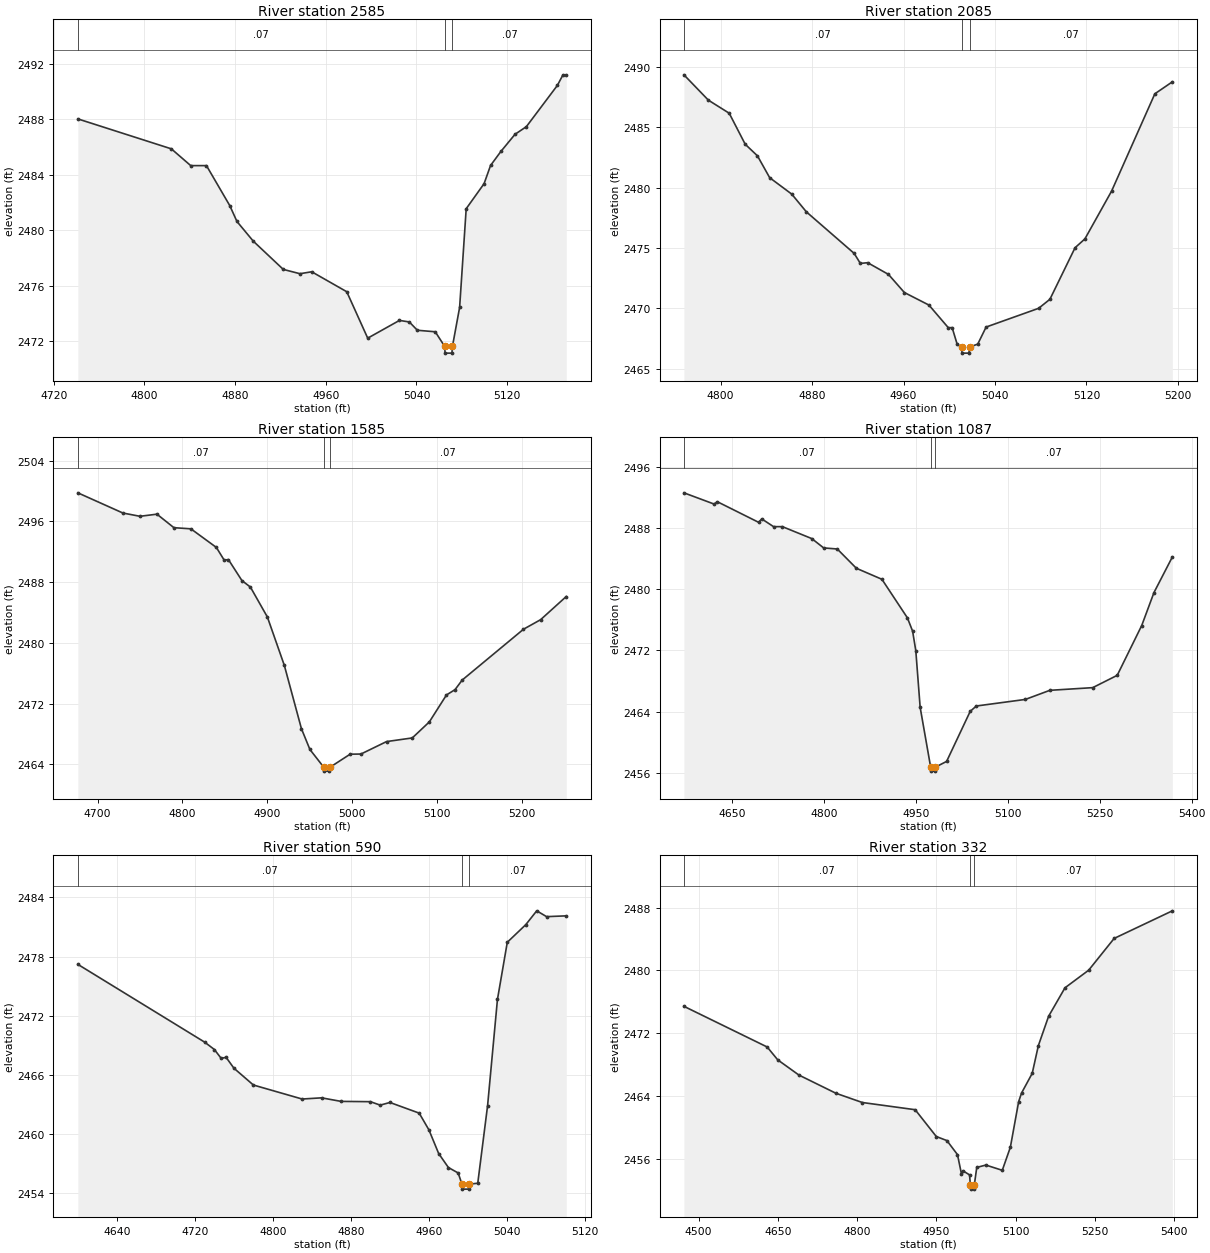
Type RM Length L Ch R = 1,2585,500,500,500
BEGIN DESCRIPTION:
Sweetwater Creek Trib 4 4.0
END DESCRIPTION:
XS GIS Cut Line= 3
      1361805.01      6787687.97      1361868.97      6787437.20
      1361954.99      6787288.02
#Sta/Elev= 30
  4741.2 2488.03  4823.7 2485.87  4840.8 2484.66  4854.7 2484.66  4875.3 2481.77
  4881.6 2480.63  4896.0 2479.21  4922.5 2477.17  4937.2 2476.86  4947.6 2477.00
  4978.5 2475.56  4997.0 2472.21  5025.0 2473.49  5033.7 2473.38  5040.8 2472.78
  5056.6 2472.67  5064.8 2471.63  5065.3 2471.13  5071.3 2471.13  5071.8 2471.63
  5078.1 2474.43  5083.9 2481.55  5099.7 2483.36  5105.4 2484.67  5114.5 2485.68
  5127.0 2486.92  5137.0 2487.47  5164.3 2490.44  5169.3 2491.21  5172.2 2491.21
#Mann=3,-1,0
  4741.2    0.07       0  5064.8    0.07       0  5071.8    0.07       0
Bank Sta=5064.8,5071.8
Exp/Cntr=0.3,0.1

Type RM Length L Ch R = 1,2085,500,500,500
BEGIN DESCRIPTION:
Sweetwater Creek Trib 4 3.0
END DESCRIPTION:
XS GIS Cut Line= 3
      1362155.00      6787937.99      1362238.32      6787721.36
      1362305.00      6787538.01
#Sta/Elev= 30
  4767.9 2489.34  4789.3 2487.24  4807.5 2486.16  4821.5 2483.59  4832.2 2482.63
  4842.9 2480.82  4862.2 2479.46  4875.0 2477.99  4916.8 2474.55  4922.2 2473.72
  4928.6 2473.78  4946.8 2472.81  4960.7 2471.31  4982.2 2470.27  4999.1 2468.40
  5002.5 2468.40  5006.9 2467.02  5010.7 2466.79  5011.2 2466.29  5017.2 2466.29
  5017.7 2466.79  5024.9 2467.04  5032.2 2468.45  5078.1 2470.00  5088.0 2470.75
  5110.0 2475.02  5118.6 2475.75  5141.9 2479.70  5179.8 2487.77  5195.1 2488.76
#Mann=3,-1,0
  4767.9    0.07       0  5010.7    0.07       0  5017.7    0.07       0
Bank Sta=5010.7,5017.7
Exp/Cntr=0.3,0.1

Type RM Length L Ch R = 1,1585,498,498,498
BEGIN DESCRIPTION:
Sweetwater Creek Trib 4 2.0
END DESCRIPTION:
XS GIS Cut Line= 3
      1362671.90      6788211.08      1362686.73      6787888.22
      1362655.00      6787638.02
#Sta/Elev= 30
  4676.8 2499.76  4729.9 2497.10  4750.0 2496.67  4770.0 2496.95  4790.0 2495.17
  4810.0 2495.02  4840.0 2492.57  4849.2 2490.90  4854.2 2490.97  4870.1 2488.21
  4880.1 2487.35  4900.1 2483.41  4920.1 2477.03  4940.2 2468.71  4950.2 2465.97
  4966.6 2463.62  4967.1 2463.12  4973.2 2463.12  4973.7 2463.62  4997.6 2465.35
  5010.3 2465.37  5040.5 2467.01  5070.8 2467.49  5090.9 2469.60  5111.1 2473.15
  5121.2 2473.85  5129.6 2475.11  5201.8 2481.80  5222.0 2483.06  5252.2 2486.11
#Mann=3,-1,0
  4676.8    0.07       0  4966.6    0.07       0  4973.7    0.07       0
Bank Sta=4966.6,4973.7
Exp/Cntr=0.3,0.1

Type RM Length L Ch R = 1,1087,497,497,497
BEGIN DESCRIPTION:
Sweetwater Creek Trib 4 1.0
END DESCRIPTION:
XS GIS Cut Line= 3
      1363224.12      6788318.57      1363105.58      6787906.48
      1363105.00      6787537.98
#Sta/Elev= 30
  4571.2 2492.58  4620.5 2491.11  4625.7 2491.42  4693.0 2488.73  4698.3 2489.17
  4717.5 2488.16  4731.9 2488.16  4779.9 2486.60  4799.3 2485.38  4821.5 2485.24
  4852.7 2482.72  4894.4 2481.28  4936.0 2476.24  4944.5 2474.50  4949.7 2471.95
  4956.8 2464.55  4974.0 2456.71  4974.5 2456.21  4980.7 2456.21  4981.2 2456.71
  5000.0 2457.48  5038.5 2464.02  5048.5 2464.72  5128.5 2465.58  5168.5 2466.77
  5238.5 2467.12  5278.5 2468.73  5318.5 2475.24  5338.5 2479.55  5368.5 2484.20
#Mann=3,-1,0
  4571.2    0.07       0  4974.0    0.07       0  4981.2    0.07       0
Bank Sta=4974,4981.2
Exp/Cntr=0.3,0.1

Type RM Length L Ch R = 1,590,258,258,258
BEGIN DESCRIPTION:
Sweetwater Creek Trib 4 1454
END DESCRIPTION:
XS GIS Cut Line= 3
      1363355.00      6787938.00      1363368.43      6787538.02
      1363355.00      6787438.02
#Sta/Elev= 30
  4599.8 2477.21  4729.9 2469.32  4739.9 2468.57  4746.9 2467.67  4751.9 2467.78
  4759.9 2466.68  4779.9 2464.97  4829.9 2463.55  4849.9 2463.67  4869.9 2463.31
  4900.0 2463.28  4910.0 2462.93  4920.0 2463.20  4950.0 2462.12  4960.0 2460.42
  4970.0 2458.02  4980.0 2456.60  4990.0 2456.05  4993.9 2454.91  4994.4 2454.41
  5000.7 2454.41  5001.2 2454.91  5010.1 2455.01  5020.2 2462.89  5030.3 2473.65
  5040.4 2479.45  5059.4 2481.24  5070.6 2482.64  5080.7 2482.05  5100.9 2482.13
#Mann=3,-1,0
  4599.8    0.07       0  4993.9    0.07       0  5001.2    0.07       0
Bank Sta=4993.9,5001.2
Exp/Cntr=0.3,0.1

Type RM Length L Ch R = 1,332,0,0,0
BEGIN DESCRIPTION:
Sweetwater Creek Trib 4 4509
END DESCRIPTION:
XS GIS Cut Line= 3
      1363589.74      6788015.49      1363610.00      6787487.98
      1363235.56      6787356.66
#Sta/Elev= 30
  4472.1 2475.43  4629.7 2470.24  4649.7 2468.60  4689.8 2466.66  4759.8 2464.34
  4809.8 2463.16  4909.9 2462.24  4949.9 2458.82  4970.0 2458.30  4990.0 2456.51
  4997.5 2454.05  5000.0 2454.46  5012.8 2453.93  5014.5 2452.61  5015.0 2452.11
  5021.3 2452.11  5021.8 2452.61  5026.5 2454.88  5043.8 2455.18  5074.8 2454.51
  5090.1 2457.45  5105.8 2463.27  5111.3 2464.37  5131.5 2466.88  5143.1 2470.41
  5162.5 2474.16  5193.5 2477.79  5238.4 2480.04  5286.6 2484.09  5396.8 2487.61
#Mann=3,-1,0
  4472.1    0.07       0  5014.5    0.07       0  5021.8    0.07       0
Bank Sta=5014.5,5021.8
Exp/Cntr=0.3,0.1

Chan Stop Cuts=-1