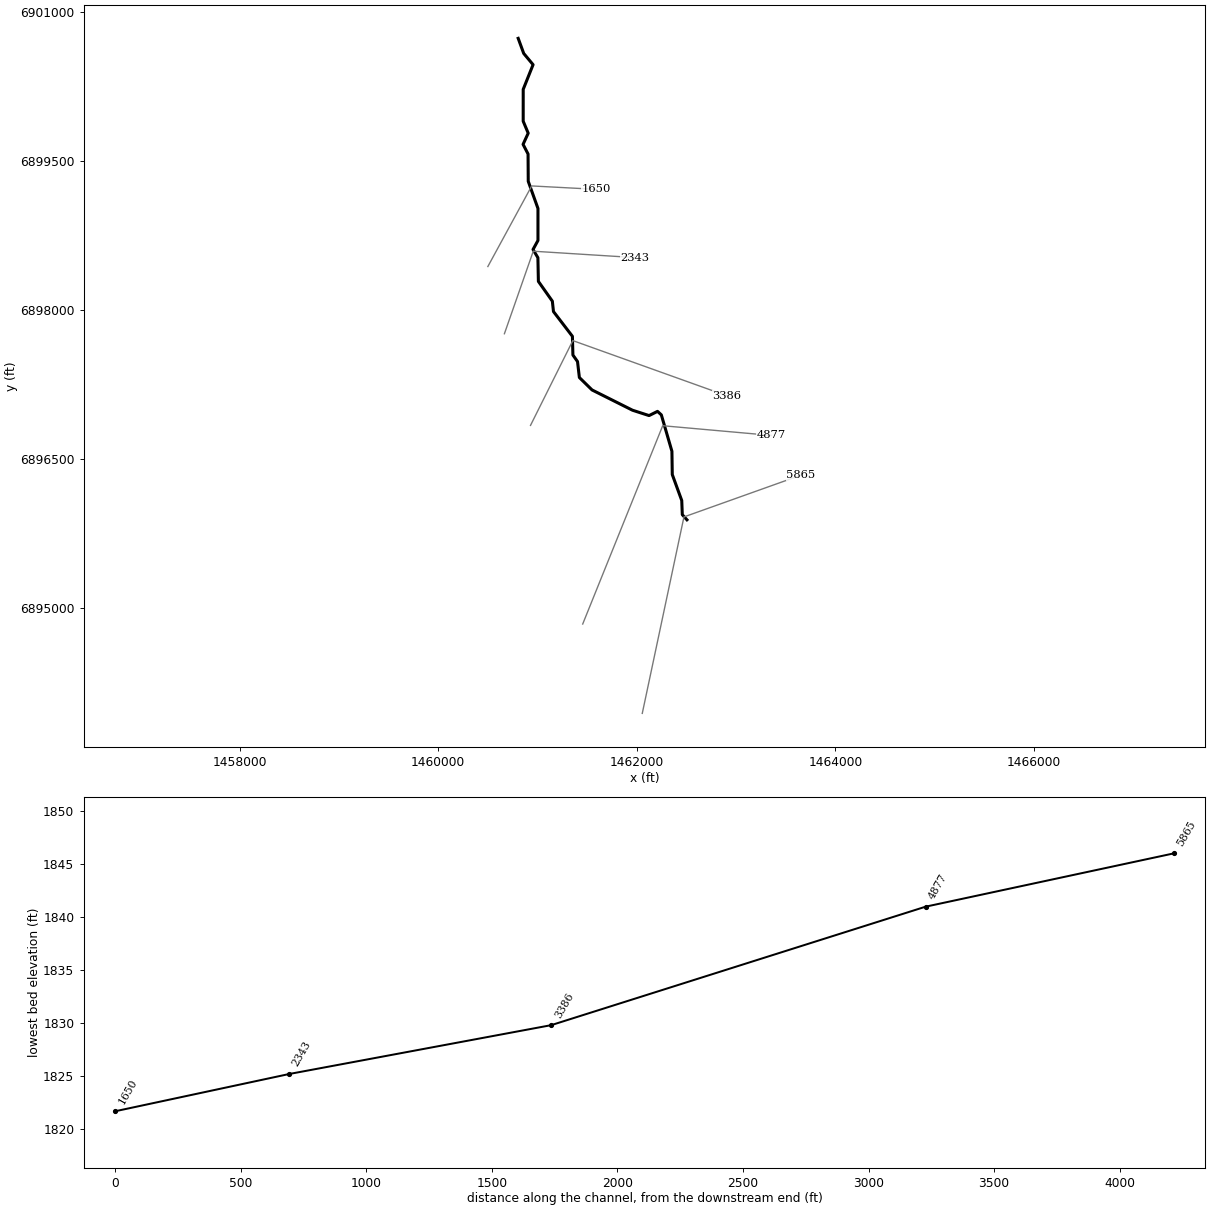
--- Sweetwater Creek Trib 40.prj (project) ---

Proj Title=Sweetwater Creek Trib 40 Base Level Engineering
Current Plan=p01
Default Exp/Contr=0.3,0.1
English Units
Geom File=g01
Flow File=f01
Plan File=p01
Y Axis Title=Elevation
X Axis Title(PF)=Main Channel Distance
X Axis Title(XS)=Station
BEGIN DESCRIPTION:
Sweetwater Creek Trib 40
END DESCRIPTION:
DSS Export Rating Curves= 0
DSS Export Rating Curve Sorted= 0
DSS Export Volume Flow Curves= 0
DXF OffsetX= 0
DXF OffsetY= 0
DXF ScaleX= 1
DXF ScaleY= 10

--- Sweetwater Creek Trib 40.p01 (plan) ---

Plan Title=Multiple Run
Short Identifier=Multiple
Geom File=g01
Flow File=f01
Subcritical Flow
K Sum by GR= 0
Std Step Tol= 0.01
Critical Tol= 0.01
Num of Std Step Trials= 20
Max Error Tol= 0.3
Flow Tol Ratio= 0.001
Split Flow NTrial= 30
Split Flow Tol= 0.02
Split Flow Ratio= 0.02
Log Output Level= 0
Friction Slope Method= 1
Unsteady Friction Slope Method= 2
Unsteady Bridges Friction Slope Method= 1
Parabolic Critical Depth
Global Vel Dist=  1 , 1 , 1
Global Log Level= 0
CheckData=True
Encroach Param= -1, 0, 0, 0
BEGIN DESCRIPTION:
Multiple Run
END DESCRIPTION:

--- Sweetwater Creek Trib 40.f01 (steady flow) ---

Flow Title=Multiple
Number of Profiles=7
Profile Names=10-year,25-year,50-year,1pct_min,100-year,1pct_plu,500-year
River Rch & RM= Sweetwater Creek,Reach-1,5865
     323     451     556     341     679    1356    1028
Boundary for River Rch & Prof#=Sweetwater Creek,Reach-1,1
Up Type=0
Dn Type=3
Dn Slope=0.005
Boundary for River Rch & Prof#=Sweetwater Creek,Reach-1,2
Up Type=0
Dn Type=3
Dn Slope=0.005
Boundary for River Rch & Prof#=Sweetwater Creek,Reach-1,3
Up Type=0
Dn Type=3
Dn Slope=0.005
Boundary for River Rch & Prof#=Sweetwater Creek,Reach-1,4
Up Type=0
Dn Type=3
Dn Slope=0.005
Boundary for River Rch & Prof#=Sweetwater Creek,Reach-1,5
Up Type=0
Dn Type=3
Dn Slope=0.005
Boundary for River Rch & Prof#=Sweetwater Creek,Reach-1,6
Up Type=0
Dn Type=3
Dn Slope=0.005
Boundary for River Rch & Prof#=Sweetwater Creek,Reach-1,7
Up Type=0
Dn Type=3
Dn Slope=0.005

--- Sweetwater Creek Trib 40.g01 (geometry) ---

Geom Title=Existing Conditions

River Reach=Sweetwater Creek,Reach-1
Reach XY= 30
      1462505.00      6895888.00      1462458.30      6895939.37
      1462452.62      6896082.47      1462357.26      6896343.94
      1462353.62      6896578.34      1462247.15      6896944.81
      1462208.69      6896980.30      1462123.46      6896937.89
      1461956.58      6896991.83      1461548.94      6897196.14
      1461421.43      6897321.23      1461402.73      6897482.06
      1461356.38      6897547.66      1461351.25      6897736.45
      1461160.52      6897985.57      1461149.23      6898090.32
      1461008.55      6898289.47      1461003.60      6898528.35
      1460954.62      6898610.81      1461004.30      6898701.91
      1461004.32      6899024.08      1460906.38      6899297.66
      1460904.48      6899572.79      1460854.28      6899669.98
      1460905.91      6899782.61      1460855.52      6899903.21
      1460855.68      6900224.08      1460955.04      6900472.66
      1460860.83      6900585.70      1460805.00      6900738.00

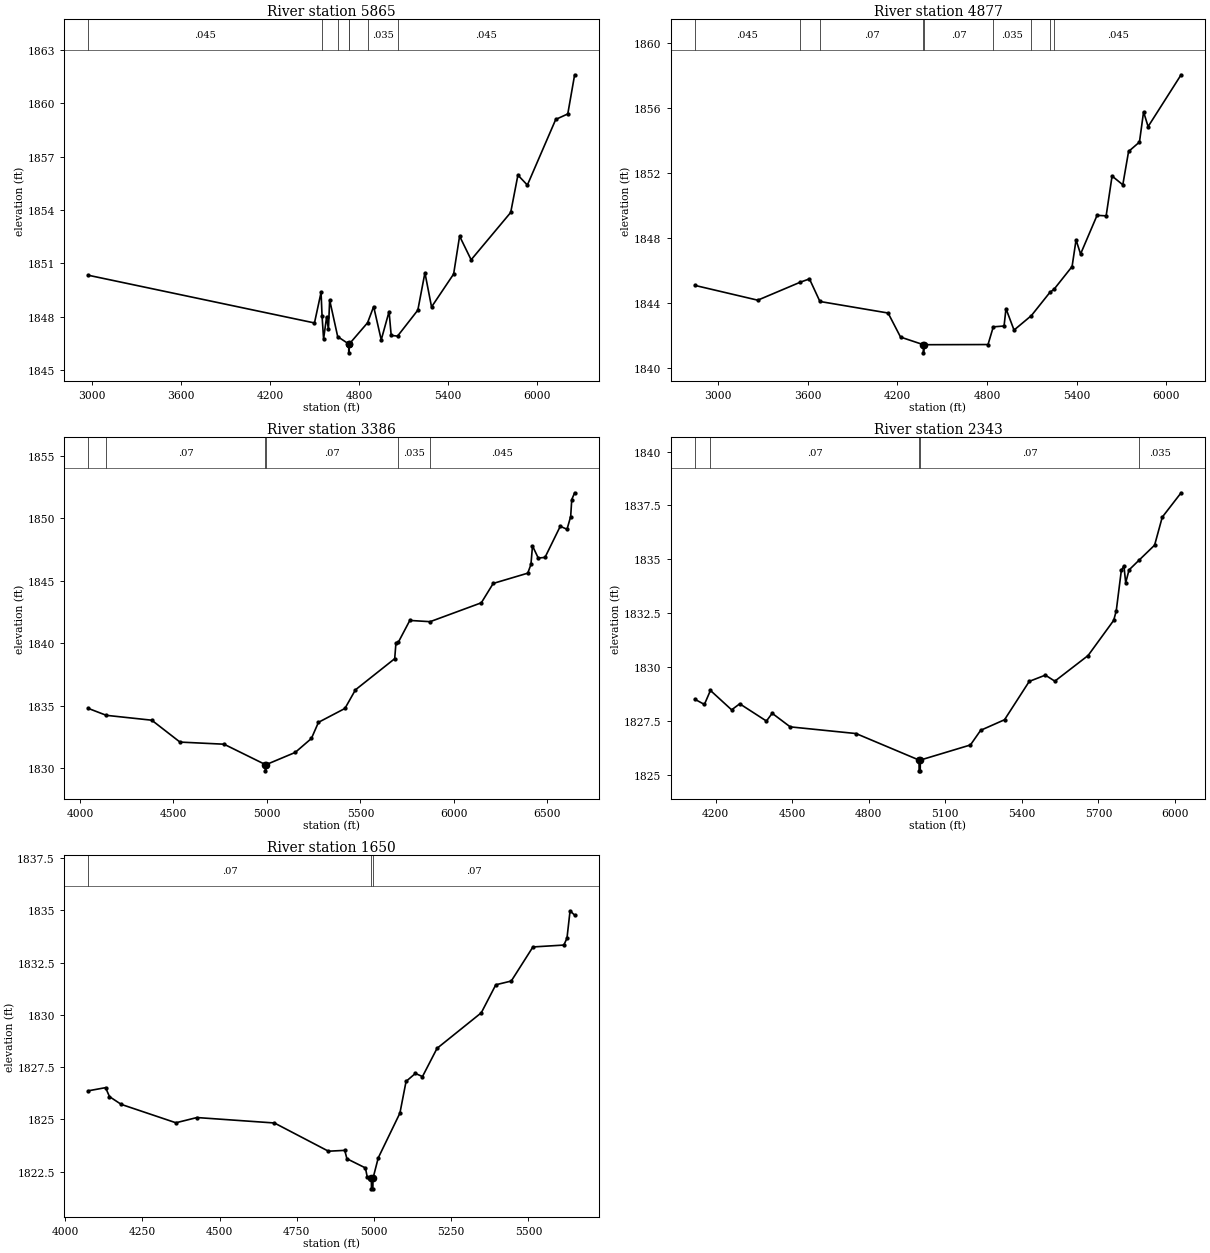
Type RM Length L Ch R = 1,5865,988,988,988
BEGIN DESCRIPTION:
Sweetwater Creek Trib 40 6.0
END DESCRIPTION:
XS GIS Cut Line= 3
      1462055.00      6893938.02      1462474.87      6895916.97
      1463655.02      6896338.01
#Sta/Elev= 30
  2977.0 1850.33  4500.1 1847.65  4544.5 1849.37  4551.1 1848.06  4561.5 1846.75
  4581.9 1847.99  4594.2 1847.29  4602.4 1848.94  4656.6 1846.88  4730.8 1846.47
  4731.1 1845.97  4735.0 1846.47  4857.8 1847.66  4898.8 1848.57  4949.9 1846.70
  5002.7 1848.29  5017.0 1846.95  5059.9 1846.91  5196.5 1848.37  5244.3 1850.47
  5288.9 1848.55  5437.7 1850.40  5477.9 1852.53  5555.6 1851.20  5822.2 1853.86
  5870.8 1855.96  5934.5 1855.40  6125.6 1859.09  6206.8 1859.40  6253.0 1861.60
#Mann=7,-1,0
  2977.0   0.045       0  4551.1   0.035       0  4656.6    0.07       0
  4730.8   0.035       0  4735.0    0.07       0  4857.8   0.035       0
  5059.9   0.045       0
Bank Sta=4730.8,4735
Exp/Cntr=0.3,0.1

Type RM Length L Ch R = 1,4877,1491,1491,1491
BEGIN DESCRIPTION:
Sweetwater Creek Trib 40 5.0
END DESCRIPTION:
XS GIS Cut Line= 3
      1461455.00      6894838.00      1462260.81      6896835.70
      1463354.96      6896738.00
#Sta/Elev= 30
  2845.9 1845.10  3266.4 1844.19  3549.1 1845.29  3612.3 1845.50  3682.4 1844.11
  4138.4 1843.40  4221.7 1841.92  4374.9 1841.45  4375.2 1840.95  4379.2 1841.45
  4806.9 1841.46  4842.1 1842.55  4914.2 1842.60  4927.0 1843.67  4980.9 1842.35
  5096.8 1843.24  5220.8 1844.67  5249.2 1844.87  5369.2 1846.26  5395.8 1847.90
  5425.9 1847.03  5536.3 1849.41  5597.1 1849.38  5636.7 1851.83  5708.5 1851.29
  5747.1 1853.34  5819.9 1853.92  5847.5 1855.78  5877.7 1854.87  6098.5 1858.06
#Mann=9,-1,0
  2845.9   0.045       0  3549.1   0.035       0  3682.4    0.07       0
  4374.9   0.035       0  4379.2    0.07       0  4842.1   0.035       0
  5096.8   0.045       0  5220.8   0.035       0  5249.2   0.045       0
Bank Sta=4374.9,4379.2
Exp/Cntr=0.3,0.1

Type RM Length L Ch R = 1,3386,1043,1043,1043
BEGIN DESCRIPTION:
Sweetwater Creek Trib 40 0.1
END DESCRIPTION:
XS GIS Cut Line= 3
      1460929.23      6896838.90      1461355.44      6897693.18
      1462904.98      6897138.01
#Sta/Elev= 30
  4045.3 1834.78  4141.0 1834.23  4384.1 1833.84  4535.1 1832.09  4770.7 1831.92
  4992.0 1830.29  4992.3 1829.79  4996.4 1830.29  5151.2 1831.26  5238.1 1832.38
  5275.7 1833.67  5417.4 1834.78  5473.6 1836.27  5683.6 1838.76  5690.0 1839.98
  5703.1 1840.08  5764.4 1841.82  5873.0 1841.72  6146.8 1843.23  6210.5 1844.78
  6395.2 1845.60  6412.3 1846.30  6420.6 1847.78  6451.4 1846.81  6487.5 1846.86
  6569.1 1849.35  6605.2 1849.11  6624.8 1850.13  6630.6 1851.49  6646.0 1852.03
#Mann=6,-1,0
  4045.3   0.035       0  4141.0    0.07       0  4992.0    0.07       0
  4996.4    0.07       0  5703.1   0.035       0  5873.0   0.045       0
Bank Sta=4992,4996.4
Exp/Cntr=0.3,0.1

Type RM Length L Ch R = 1,2343,693,693,693
BEGIN DESCRIPTION:
Sweetwater Creek Trib 40 4395
END DESCRIPTION:
XS GIS Cut Line= 3
      1460666.18      6897762.18      1460956.94      6898593.71
      1461978.63      6898529.52
#Sta/Elev= 30
  4119.1 1828.51  4156.4 1828.27  4180.0 1828.92  4263.0 1828.02  4294.8 1828.30
  4399.4 1827.50  4421.9 1827.86  4492.5 1827.23  4750.3 1826.92  4997.1 1825.69
  4997.5 1825.19  5001.8 1825.19  5002.2 1825.69  5198.4 1826.39  5238.5 1827.07
  5332.0 1827.56  5428.9 1829.34  5491.9 1829.63  5529.1 1829.35  5659.4 1830.54
  5759.6 1832.17  5769.6 1832.61  5789.6 1834.49  5799.6 1834.70  5806.7 1833.92
  5819.7 1834.51  5857.8 1834.95  5919.9 1835.66  5949.9 1836.96  6023.7 1838.09
#Mann=5,-1,0
  4119.1   0.035       0  4180.0    0.07       0  4997.1    0.07       0
  5002.2    0.07       0  5857.8   0.035       0
Bank Sta=4997.1,5002.2
Exp/Cntr=0.3,0.1

Type RM Length L Ch R = 1,1650,0,0,0
BEGIN DESCRIPTION:
Sweetwater Creek Trib 40 4396
END DESCRIPTION:
XS GIS Cut Line= 3
      1460499.49      6898439.22      1460941.20      6899251.14
      1461589.81      6899217.01
#Sta/Elev= 30
  4075.7 1826.37  4131.2 1826.52  4143.9 1826.09  4181.9 1825.72  4358.9 1824.84
  4427.0 1825.09  4677.7 1824.83  4852.6 1823.48  4905.4 1823.52  4912.4 1823.12
  4972.3 1822.68  4978.0 1822.26  4991.5 1822.18  4991.9 1821.68  4996.4 1821.68
  4996.8 1822.18  5013.8 1823.16  5083.9 1825.30  5103.9 1826.82  5134.0 1827.20
  5157.0 1827.05  5204.1 1828.40  5347.3 1830.10  5394.3 1831.44  5444.4 1831.62
  5514.5 1833.25  5614.6 1833.34  5624.7 1833.67  5634.7 1834.98  5649.5 1834.77
#Mann=3,-1,0
  4075.7    0.07       0  4991.5    0.07       0  4996.8    0.07       0
Bank Sta=4991.5,4996.8
Exp/Cntr=0.3,0.1

Chan Stop Cuts=-1