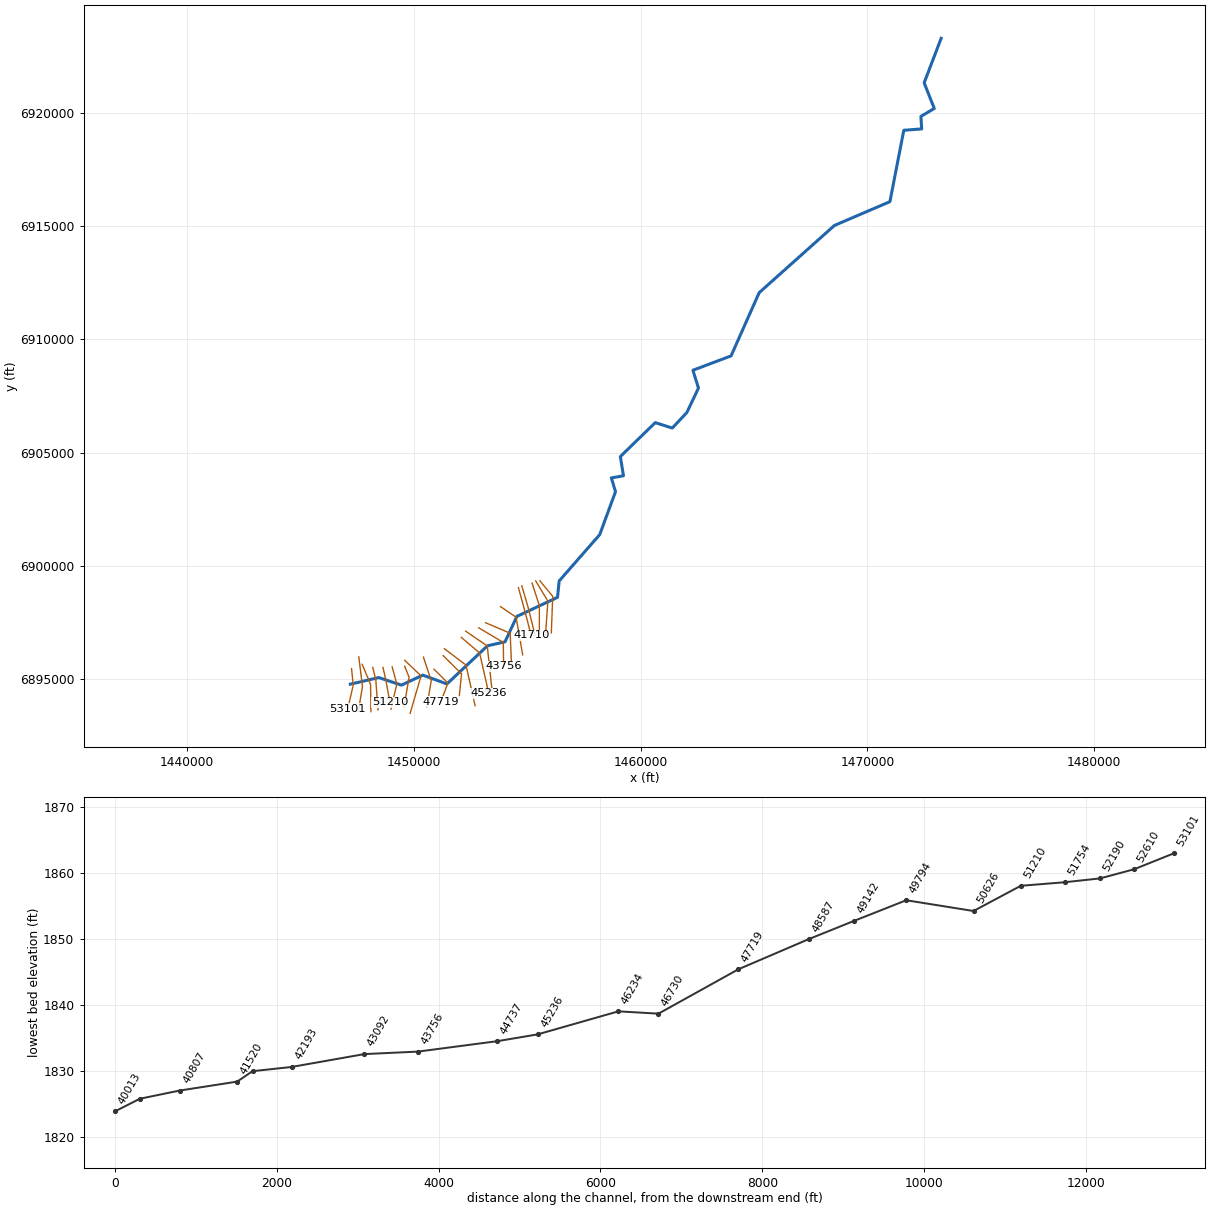
--- Sweetwater Creek Trib 41.prj (project) ---

Proj Title=Sweetwater Creek Trib 41 Base Level Engineering
Current Plan=p01
Default Exp/Contr=0.3,0.1
English Units
Geom File=g01
Flow File=f01
Plan File=p01
Y Axis Title=Elevation
X Axis Title(PF)=Main Channel Distance
X Axis Title(XS)=Station
BEGIN DESCRIPTION:
Sweetwater Creek Trib 41
END DESCRIPTION:
DSS Export Rating Curves= 0
DSS Export Rating Curve Sorted= 0
DSS Export Volume Flow Curves= 0
DXF OffsetX= 0
DXF OffsetY= 0
DXF ScaleX= 1
DXF ScaleY= 10

--- Sweetwater Creek Trib 41.p01 (plan) ---

Plan Title=Multiple Run
Short Identifier=Multiple
Geom File=g01
Flow File=f01
Subcritical Flow
K Sum by GR= 0
Std Step Tol= 0.01
Critical Tol= 0.01
Num of Std Step Trials= 20
Max Error Tol= 0.3
Flow Tol Ratio= 0.001
Split Flow NTrial= 30
Split Flow Tol= 0.02
Split Flow Ratio= 0.02
Log Output Level= 0
Friction Slope Method= 1
Unsteady Friction Slope Method= 2
Unsteady Bridges Friction Slope Method= 1
Parabolic Critical Depth
Global Vel Dist=  1 , 1 , 1
Global Log Level= 0
CheckData=True
Encroach Param= -1, 0, 0, 0
BEGIN DESCRIPTION:
Multiple Run
END DESCRIPTION:

--- Sweetwater Creek Trib 41.f01 (steady flow) ---

Flow Title=Multiple
Program Version=4.10
Number of Profiles= 7
Profile Names=10-year,25-year,50-year,1pct_min,100-year,1pct_plu,500-year
River Rch & RM=Sweetwater Creek,Reach-1         ,53101
     353     497     617     380     758    1513    1161
River Rch & RM=Sweetwater Creek,Reach-1         ,46234
     483     687     859     532    1062    2119    1645
River Rch & RM=Sweetwater Creek,Reach-1         ,42193
     585     839    1054     656    1310    2613    2049
Boundary for River Rch & Prof#=Sweetwater Creek,Reach-1         , 1
Up Type= 0
Dn Type= 3
Dn Slope=0.005
Boundary for River Rch & Prof#=Sweetwater Creek,Reach-1         , 2
Up Type= 0
Dn Type= 3
Dn Slope=0.005
Boundary for River Rch & Prof#=Sweetwater Creek,Reach-1         , 3
Up Type= 0
Dn Type= 3
Dn Slope=0.005
Boundary for River Rch & Prof#=Sweetwater Creek,Reach-1         , 4
Up Type= 0
Dn Type= 3
Dn Slope=0.005
Boundary for River Rch & Prof#=Sweetwater Creek,Reach-1         , 5
Up Type= 0
Dn Type= 3
Dn Slope=0.005
Boundary for River Rch & Prof#=Sweetwater Creek,Reach-1         , 6
Up Type= 0
Dn Type= 3
Dn Slope=0.005
Boundary for River Rch & Prof#=Sweetwater Creek,Reach-1         , 7
Up Type= 0
Dn Type= 3
Dn Slope=0.005
DSS Import GetInterval= 0
DSS Import GetPeak= 0
DSS Import FillOption= 0

--- Sweetwater Creek Trib 41.g01 (geometry) ---

Geom Title=Existing Conditions
Program Version=4.10

River Reach=Sweetwater Creek,Reach-1
Reach XY= 30
        1447205.        6894788.      1448454.92       6895080.7
      1449455.01      6894745.53      1450399.96      6895188.85
      1451461.75       6894797.1      1453248.95       6896480.5
      1454025.18      6896657.78      1454544.95      6897777.38
      1456338.75      6898620.69      1456412.76      6899344.17
      1458201.24      6901389.56      1458897.02      6903284.67
       1458712.6      6903891.34      1459247.18      6903984.59
      1459110.07      6904832.92      1460648.81      6906330.19
      1461399.57      6906090.16      1462041.48      6906774.58
       1462554.5      6907853.21      1462310.08      6908640.32
      1463991.39      6909274.76      1465231.49      6912065.01
      1468549.25      6915030.66      1470997.18      6916081.81
      1471608.23      6919230.01      1472397.09      6919290.92
      1472363.13      6919844.07      1472953.12      6920193.68
      1472505.52      6921322.78        1473255.        6923288.

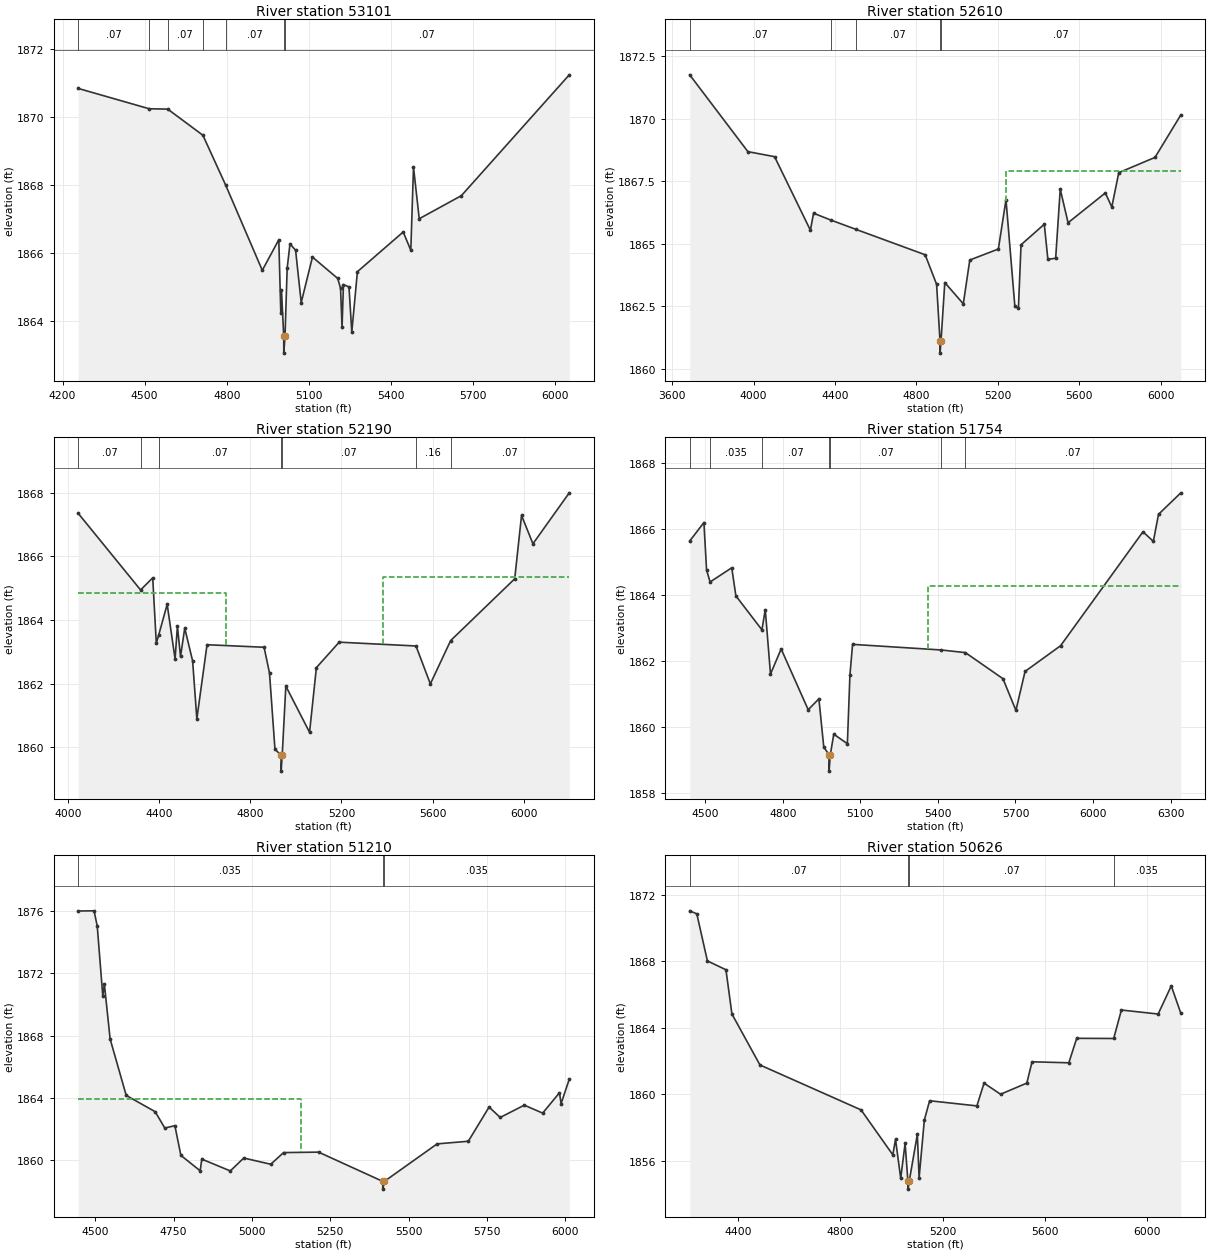
Type RM Length L Ch R = 1 ,53101   ,491,491,491
BEGIN DESCRIPTION:
Sweetwater Creek Trib 41 67.0
END DESCRIPTION:
XS GIS Cut Line= 3
      1447256.48       6895477.6      1447330.03      6894738.05
      1447092.44      6893714.05
#Sta/Elev= 30
  4256.8 1870.84  4516.6 1870.24  4584.2 1870.23  4712.7 1869.46  4795.4    1868
  4929.7 1865.48    4990 1866.38  4997.4 1864.21  4999.8  1864.9    5008 1863.54
  5008.3 1863.04  5012.7 1863.54  5020.6 1865.54  5030.9 1866.26  5051.4 1866.07
  5071.9 1864.53    5113 1865.87  5205.4 1865.24  5215.6 1864.95  5221.1  1863.8
  5226.2 1865.06  5246.4 1864.99  5256.7 1863.66  5277.2 1865.44  5444.6 1866.61
  5472.3 1866.07  5482.1 1868.52  5503.1    1867  5657.1 1867.68  6051.2 1871.24
#Mann= 7 ,-1 , 0
  4256.8     .07       0  4516.6    .035       0  4584.2     .07       0
  4712.7    .035       0  4795.4     .07       0    5008     .07       0
  5012.7     .07       0
Bank Sta=5008,5012.7
XS Rating Curve= 0 ,0
Exp/Cntr=0.3,0.1

Type RM Length L Ch R = 1 ,52610   ,420,420,420
BEGIN DESCRIPTION:
Sweetwater Creek Trib 41 66.0
END DESCRIPTION:
XS GIS Cut Line= 3
      1447576.32       6895991.9       1447739.6      6894688.09
      1447559.95      6893603.26
#Sta/Elev= 30
    3686 1871.75  3972.1 1868.68  4103.1 1868.48  4279.2 1865.54  4294.6 1866.22
  4378.6 1865.95  4504.8 1865.57  4843.1 1864.56  4899.3 1863.38    4916 1861.13
  4916.4 1860.63  4921.1 1861.13  4939.6 1863.45  5030.5  1862.6  5062.4 1864.35
  5202.8 1864.79  5240.3 1866.76  5283.9  1862.5  5301.4 1862.43  5314.3 1864.96
  5428.5 1865.78  5446.1 1864.38  5484.4 1864.42  5506.9 1867.18  5545.4 1865.84
  5728.4 1867.03  5760.3 1866.47  5794.5 1867.84  5972.5 1868.45  6099.6 1870.15
#Mann= 5 ,-1 , 0
    3686     .07       0  4378.6    .035       0  4504.8     .07       0
    4916     .07       0  4921.1     .07       0
#XS Ineff= 2 , 0
                         5239.09          1867.9
Permanent Ineff=
       F       F
Bank Sta=4916,4921.1
XS Rating Curve= 0 ,0
Exp/Cntr=0.3,0.1

Type RM Length L Ch R = 1 ,52190   ,436,436,436
BEGIN DESCRIPTION:
Sweetwater Creek Trib 41 65.2
END DESCRIPTION:
XS GIS Cut Line= 3
      1447728.61       6895660.4      1448095.15      6894777.89
      1448111.75      6893578.61
#Sta/Elev= 30
  4044.4 1867.35  4318.5 1864.94  4371.8 1865.32  4387.5 1863.27  4398.7 1863.54
  4435.2 1864.49  4469.9 1862.77  4480.1  1863.8  4493.8 1862.85  4512.3 1863.74
  4546.9 1862.71  4565.4 1860.89  4610.1 1863.22  4860.4 1863.14  4884.2 1862.33
  4908.1 1859.94  4934.8 1859.75  4935.2 1859.25    4940 1859.75  4955.8 1861.92
  5059.9 1860.47  5089.9  1862.5  5189.9  1863.3  5526.9 1863.18  5589.9 1861.99
    5679 1863.35    5960 1865.29    5990 1867.28    6040 1866.39  6199.4 1867.99
#Mann= 7 ,-1 , 0
  4044.4     .07       0  4318.5    .035       0  4398.7     .07       0
  4934.8     .07       0    4940     .07       0  5526.9     .16       0
    5679     .07       0
#XS Ineff= 2 , 0
         4695.43 1864.83 5380.71         1865.35
Permanent Ineff=
       F       F
Bank Sta=4934.8,4940
XS Rating Curve= 0 ,0
Exp/Cntr=0.3,0.1

Type RM Length L Ch R = 1 ,51754   ,544,544,544
BEGIN DESCRIPTION:
Sweetwater Creek Trib 41 65.1
END DESCRIPTION:
XS GIS Cut Line= 3
      1448191.16      6895531.38       1448325.2      6894987.66
      1448424.75      6893651.86
#Sta/Elev= 30
    4440 1865.64    4495  1866.2  4505.3 1864.76    4519  1864.4  4602.7 1864.83
  4618.6 1863.98  4719.3 1862.95  4732.3 1863.56  4752.5 1861.61  4793.7 1862.37
  4898.3 1860.53  4939.7 1860.86  4958.5  1859.4  4978.5 1859.17    4979 1858.67
  4983.9 1859.17  4997.2 1859.79  5049.8  1859.5  5059.7 1861.58  5069.9 1862.51
  5412.5 1862.34  5506.2 1862.26  5651.5 1861.47  5701.6 1860.51    5737 1861.69
  5874.5 1862.47    6193 1865.92  6233.1 1865.63  6253.1 1866.45  6339.5  1867.1
#Mann= 7 ,-1 , 0
    4440     .07       0    4519    .035       0  4719.3     .07       0
  4978.5     .07       0  4983.9     .07       0  5412.5     .16       0
  5506.2     .07       0
#XS Ineff= 2 , 0
                         5360.41         1864.28
Permanent Ineff=
       F       F
Bank Sta=4978.5,4983.9
XS Rating Curve= 0 ,0
Exp/Cntr=0.3,0.1

Type RM Length L Ch R = 1 ,51210   ,584,584,584
BEGIN DESCRIPTION:
Sweetwater Creek Trib 41 65.0
END DESCRIPTION:
XS GIS Cut Line= 3
      1448641.95      6895527.57       1448765.7      6894987.26
      1448945.34      6893991.23
#Sta/Elev= 30
  4445.7 1876.02  4496.6 1876.03  4506.8 1875.04  4524.4 1870.56  4529.5 1871.31
  4547.8 1867.79  4599.1 1864.16  4691.5 1863.11  4722.2 1862.06  4754.3 1862.21
  4773.5  1860.3    4835 1859.31  4840.2 1860.06  4931.1  1859.3    4974 1860.13
  5060.2 1859.73  5100.9 1860.48  5212.6 1860.51  5417.1 1858.63  5417.5 1858.13
  5422.5 1858.63  5590.6 1861.04  5690.2 1861.21  5756.4 1863.41  5791.8 1862.74
  5868.7 1863.53  5927.3 1863.02  5980.9 1864.33    5986 1863.63  6012.1  1865.2
#Mann= 3 ,-1 , 0
  4445.7    .035       0  5417.1    .035       0  5422.5    .035       0
#XS Ineff= 2 , 0
         5156.55  1863.9
Permanent Ineff=
       F       F
Bank Sta=5417.1,5422.5
XS Rating Curve= 0 ,0
Exp/Cntr=0.3,0.1

Type RM Length L Ch R = 1 ,50626   ,832,832,832
BEGIN DESCRIPTION:
Sweetwater Creek Trib 41 64.0
END DESCRIPTION:
XS GIS Cut Line= 3
      1449047.77      6895554.84      1449252.55       6894793.5
      1448996.21      6893691.52
#Sta/Elev= 30
  4211.6 1871.03  4239.4 1870.85  4280.8 1868.02  4353.3 1867.49  4376.7 1864.83
  4486.2 1861.77  4881.4 1859.07  5005.6 1856.37  5016.1  1857.3  5036.4 1854.96
  5053.6 1857.06  5064.4 1854.81  5064.9 1854.31    5070 1854.81  5101.4  1857.6
  5108.3 1854.99  5128.8 1858.46  5149.4 1859.62  5334.2 1859.31  5362.1 1860.68
  5426.6 1860.01  5529.3 1860.68  5549.8 1861.96  5693.5  1861.9  5724.3 1863.37
  5868.9 1863.36    5899 1865.07  6042.6 1864.83  6093.9 1866.52  6131.4 1864.87
#Mann= 4 ,-1 , 0
  4211.6     .07       0  5064.4     .07       0    5070     .07       0
  5868.9    .035       0
Bank Sta=5064.4,5070
XS Rating Curve= 0 ,0
Exp/Cntr=0.3,0.1

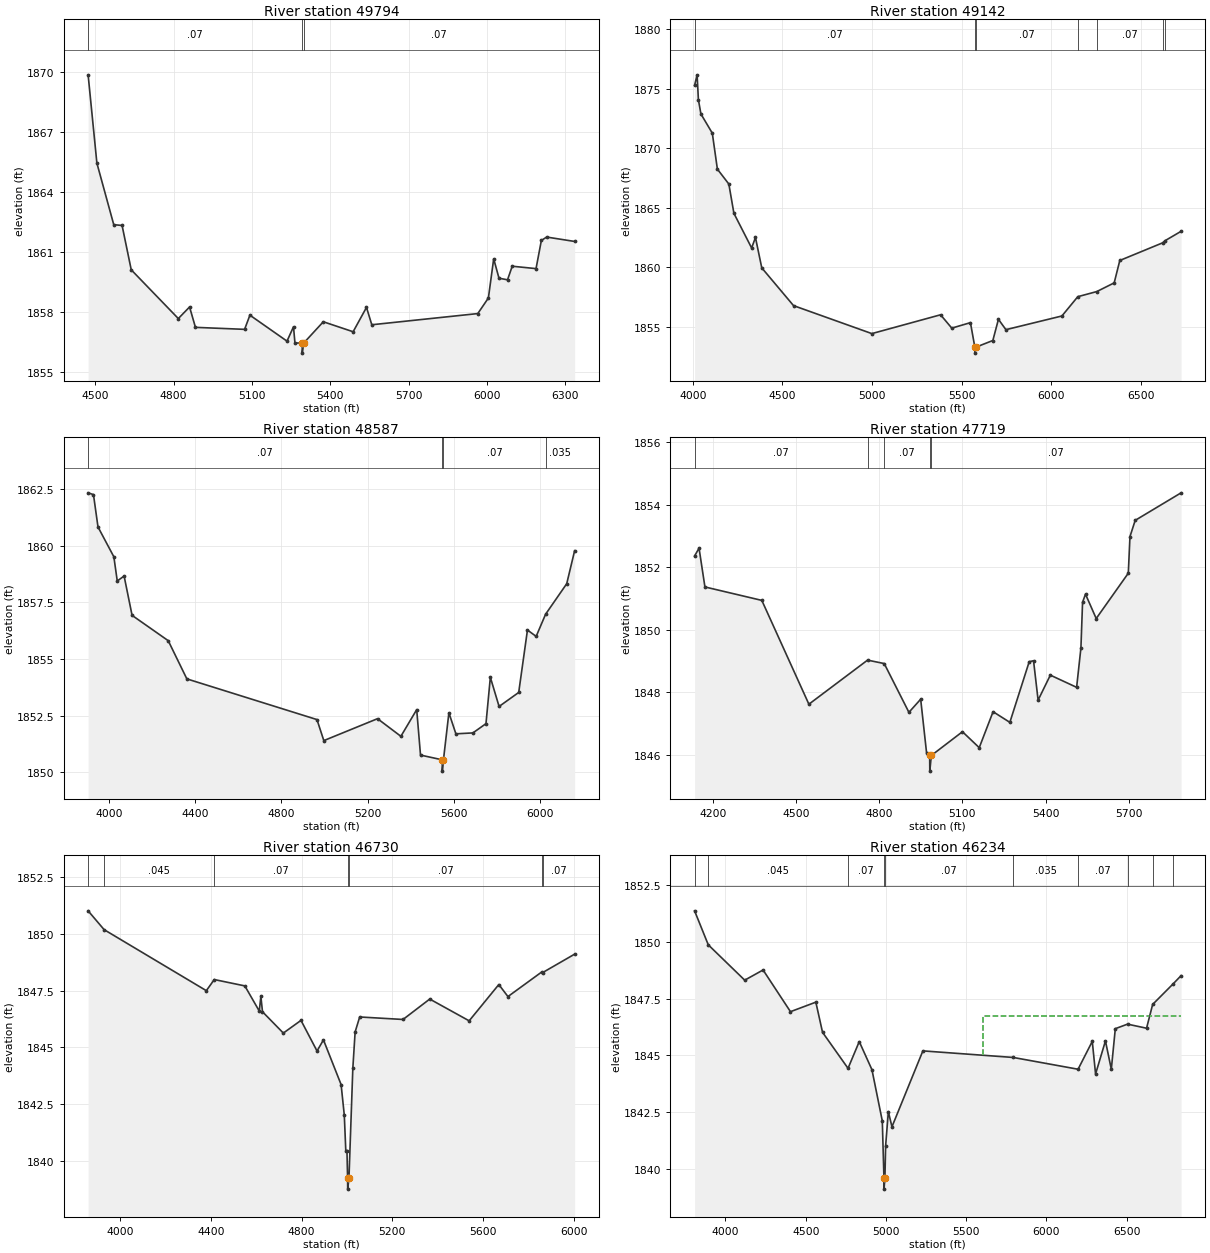
Type RM Length L Ch R = 1 ,49794   ,652,652,652
BEGIN DESCRIPTION:
Sweetwater Creek Trib 41 63.1
END DESCRIPTION:
XS GIS Cut Line= 3
       1449600.3      6895579.28      1449794.36      6895088.99
      1449565.51      6893772.53
#Sta/Elev= 30
  4472.7 1869.87  4506.3 1865.45  4570.9 1862.37  4602.8 1862.33  4637.9 1860.11
  4818.2 1857.67  4861.3 1858.25  4883.8 1857.23  5072.1 1857.13  5092.4 1857.84
  5234.5 1856.54  5259.4 1857.26  5264.9 1856.45  5292.6 1856.44    5293 1855.94
  5298.2 1856.44  5373.6 1857.51  5487.8 1857.01    5539 1858.23  5559.3 1857.36
  5965.3 1857.92  6005.9  1858.7  6026.2 1860.66  6046.5 1859.69  6079.2 1859.61
  6097.2 1860.29  6188.4 1860.17  6208.8 1861.58  6229.1 1861.75  6336.2 1861.53
#Mann= 3 ,-1 , 0
  4472.7     .07       0  5292.6     .07       0  5298.2     .07       0
Bank Sta=5292.6,5298.2
XS Rating Curve= 0 ,0
Exp/Cntr=0.3,0.1

Type RM Length L Ch R = 1 ,49142   ,555,555,555
BEGIN DESCRIPTION:
Sweetwater Creek Trib 41 63.0
END DESCRIPTION:
XS GIS Cut Line= 3
      1449604.98      6895838.02      1450321.48      6895155.14
      1449839.75       6893499.7
#Sta/Elev= 30
  4010.2 1875.26  4024.2 1876.15  4031.5 1874.06  4045.6 1872.86  4109.1 1871.25
  4137.4 1868.23  4201.3 1866.98  4229.6 1864.52  4328.4 1861.61  4349.8 1862.49
    4385 1859.94  4562.1 1856.77    4999 1854.42  5382.4    1856  5444.9 1854.88
    5549 1855.34  5573.6 1853.28  5574.1 1852.78  5579.3 1853.28    5674 1853.84
  5705.2 1855.62  5746.9 1854.75  6059.3  1855.9  6147.9 1857.52  6253.9 1857.95
  6350.9 1858.68  6382.2 1860.56  6620.9 1862.04  6635.6 1862.23  6724.1 1863.01
#Mann= 7 ,-1 , 0
  4010.2     .07       0  5573.6     .07       0  5579.3     .07       0
  6147.9    .035       0  6253.9     .07       0  6620.9    .035       0
  6635.6     .07       0
Bank Sta=5573.6,5579.3
XS Rating Curve= 0 ,0
Exp/Cntr=0.3,0.1

Type RM Length L Ch R = 1 ,48587   ,868,868,868
BEGIN DESCRIPTION:
Sweetwater Creek Trib 41 62.1
END DESCRIPTION:
XS GIS Cut Line= 3
      1450427.77      6895981.62      1450770.36      6894938.01
      1450578.38      6893791.78
#Sta/Elev= 30
  3901.6 1862.35  3926.5 1862.27  3947.5 1860.84  4021.2 1859.52    4037 1858.45
  4068.8 1858.67  4105.9 1856.93  4273.8 1855.81  4360.4 1854.12    4965 1852.32
  4996.8 1851.39  5246.4 1852.36  5354.9 1851.58  5428.4 1852.76  5446.1 1850.75
    5547 1850.54  5547.4 1850.04  5552.7 1850.54    5578 1852.62  5610.5 1851.69
  5689.5 1851.73  5750.3 1852.14  5770.6 1854.19  5811.2  1852.9  5902.4 1853.52
    5943 1856.28  5983.5    1856  6027.3 1856.98  6125.5 1858.33  6162.2 1859.79
#Mann= 4 ,-1 , 0
  3901.6     .07       0    5547     .07       0  5552.7     .07       0
  6027.3    .035       0
Bank Sta=5547,5552.7
XS Rating Curve= 0 ,0
Exp/Cntr=0.3,0.1

Type RM Length L Ch R = 1 ,47719   ,989,989,989
BEGIN DESCRIPTION:
Sweetwater Creek Trib 41 62.0
END DESCRIPTION:
XS GIS Cut Line= 3
      1450893.51       6895449.3      1451505.22      6894837.43
      1451192.91      6894005.41
#Sta/Elev= 30
  4134.8 1852.36  4150.9 1852.61  4172.1 1851.37  4377.2 1850.94  4546.9 1847.62
  4758.4 1849.03  4818.5 1848.92  4907.5 1847.36  4949.9 1847.78  4971.2 1846.06
  4982.3 1845.98  4982.8 1845.48  4988.3 1845.98  5100.5 1846.74    5161 1846.23
  5210.9 1847.38  5271.4 1847.04  5341.2 1848.98  5356.8 1849.01  5373.2 1847.75
  5417.3 1848.55  5512.1 1848.16  5527.6 1849.42  5533.5 1850.88  5544.1 1851.14
  5582.7 1850.36  5698.4 1851.81  5704.4 1852.98  5723.3  1853.5  5888.7 1854.38
#Mann= 5 ,-1 , 0
  4134.8     .07       0  4758.4    .035       0  4818.5     .07       0
  4982.3     .07       0  4988.3     .07       0
Bank Sta=4982.3,4988.3
XS Rating Curve= 0 ,0
Exp/Cntr=0.3,0.1

Type RM Length L Ch R = 1 ,46730   ,496,496,496
BEGIN DESCRIPTION:
Sweetwater Creek Trib 41 61.0
END DESCRIPTION:
XS GIS Cut Line= 3
      1451297.91      6896047.73       1452107.3       6895243.8
      1452005.35      6894245.59
#Sta/Elev= 30
  3859.2 1851.02  3929.7 1850.19  4380.2  1847.5  4415.3 1847.99  4549.9 1847.71
  4613.6  1846.6  4620.6 1847.25  4627.7 1846.57  4719.6 1845.63  4797.4 1846.19
  4868.1 1844.84  4896.4 1845.33  4974.2 1843.36  4988.3 1842.01  4994.9 1840.44
    5000 1840.44  5002.8 1839.25  5003.3 1838.75  5008.9 1839.25  5025.9 1844.08
    5036 1845.68  5056.1 1846.34  5247.1 1846.23  5364.9 1847.13  5538.6 1846.17
  5669.3 1847.77  5709.5 1847.24  5859.3 1848.33    5863  1848.3  6003.4 1849.11
#Mann= 7 ,-1 , 0
  3859.2     .07       0  3929.7    .045       0  4415.3     .07       0
  5002.8     .07       0  5008.9     .07       0  5859.3     .16       0
    5863     .07       0
Bank Sta=5002.8,5008.9
XS Rating Curve= 0 ,0
Exp/Cntr=0.3,0.1

Type RM Length L Ch R = 1 ,46234   ,998,998,998
BEGIN DESCRIPTION:
Sweetwater Creek Trib 41 60.0
END DESCRIPTION:
XS GIS Cut Line= 3
      1451351.31      6896351.75      1452302.52      6895632.54
        1452705.      6893838.02
#Sta/Elev= 30
  3807.5 1851.38  3892.8 1849.88  4119.9 1848.32  4234.3 1848.77    4405 1846.93
  4563.1 1847.35  4604.8 1846.02  4763.7 1844.43  4833.6 1845.61  4912.7 1844.37
  4977.2 1842.11  4987.5  1839.6    4988  1839.1  4993.6  1839.6    4998 1841.01
  5014.9 1842.52  5037.4 1841.85  5230.1  1845.2  5793.1 1844.91  6197.2 1844.39
  6285.7 1845.62  6306.2 1844.18  6367.7 1845.64  6404.3 1844.39  6429.2 1846.18
  6505.2 1846.38  6623.9  1846.2  6661.9 1847.25  6791.3 1848.17  6839.1 1848.52
#Mann= 10 ,-1 , 0
  3807.5    .035       0  3892.8    .045       0  4763.7     .07       0
  4987.5     .07       0  4993.6     .07       0  5793.1    .035       0
  6197.2     .07       0  6505.2    .035       0  6661.9     .07       0
  6791.3    .035       0
#XS Ineff= 2 , 0
                         5603.55         1846.76
Permanent Ineff=
       F       F
Bank Sta=4987.5,4993.6
XS Rating Curve= 0 ,0
Exp/Cntr=0.3,0.1

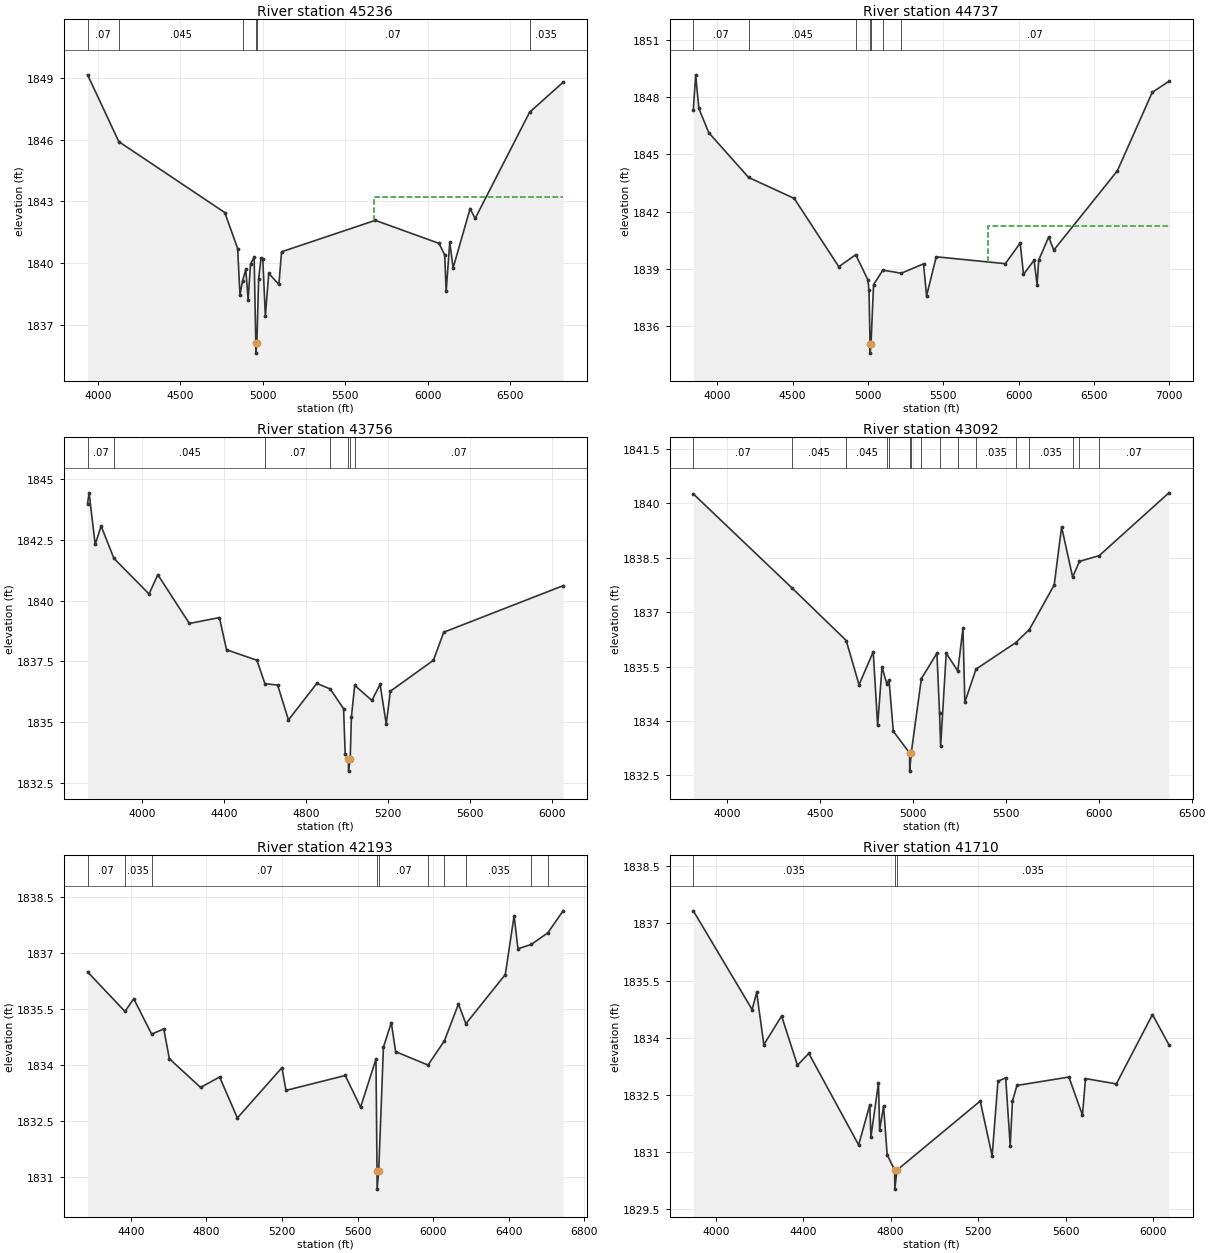
Type RM Length L Ch R = 1 ,45236   ,499,499,499
BEGIN DESCRIPTION:
Sweetwater Creek Trib 41 59.0
END DESCRIPTION:
XS GIS Cut Line= 3
      1452097.58      6896852.66      1452904.88      6896163.12
      1453305.01      6894387.96
#Sta/Elev= 30
  3938.3 1849.15  4127.6  1845.9  4769.6 1842.45  4847.6  1840.7  4861.8 1838.44
  4877.5 1839.13    4897 1839.68  4911.2 1838.21  4925.5 1839.94  4947.5 1840.29
  4957.6 1836.11  4958.1 1835.61  4963.9 1836.11  4974.9 1839.23  4989.2 1840.22
    5000 1840.19  5015.5 1837.41    5036 1839.49  5097.5 1838.95  5113.6 1840.54
  5681.8 1842.07  6067.7 1840.95  6102.1 1840.39    6111 1838.61  6132.8 1841.01
  6153.3 1839.76  6256.1 1842.64  6286.6 1842.16  6616.6 1847.33  6819.7 1848.79
#Mann= 6 ,-1 , 0
  3938.3     .07       0  4127.6    .045       0  4877.5     .07       0
  4957.6     .07       0  4963.9     .07       0  6616.6    .035       0
#XS Ineff= 2 , 0
                         5671.07         1843.19
Permanent Ineff=
       F       F
Bank Sta=4957.6,4963.9
XS Rating Curve= 0 ,0
Exp/Cntr=0.3,0.1

Type RM Length L Ch R = 1 ,44737   ,981,981,981
BEGIN DESCRIPTION:
Sweetwater Creek Trib 41 58.0
END DESCRIPTION:
XS GIS Cut Line= 3
      1452285.02       6897130.4      1453241.79      6896474.87
        1453455.      6894487.97
#Sta/Elev= 30
  3840.2 1847.34  3855.8 1849.17  3876.8 1847.41  3942.5 1846.14  4207.4 1843.79
  4510.4 1842.69  4806.3 1839.11  4918.8 1839.74  4998.9 1838.43  5006.9 1837.87
  5013.8 1835.08  5014.3 1834.58  5020.2 1835.08  5037.1 1838.17  5098.8 1838.93
  5221.5 1838.77    5369 1839.26  5389.1 1837.58  5453.2 1839.63  5912.1 1839.27
  6010.9 1840.35  6032.8 1838.71    6103 1839.45  6123.3 1838.16  6133.3 1839.45
  6200.2 1840.67  6233.9 1839.98  6656.3 1844.14  6887.6 1848.25  6998.3 1848.83
#Mann= 7 ,-1 , 0
  3840.2     .07       0  4207.4    .045       0  4918.8     .07       0
  5013.8     .07       0  5020.2     .07       0  5098.8     .16       0
  5221.5     .07       0
#XS Ineff= 2 , 0
                         5795.43         1841.24
Permanent Ineff=
       F       F
Bank Sta=5013.8,5020.2
XS Rating Curve= 0 ,0
Exp/Cntr=0.3,0.1

Type RM Length L Ch R = 1 ,43756   ,664,664,664
BEGIN DESCRIPTION:
Sweetwater Creek Trib 41 57.0
END DESCRIPTION:
XS GIS Cut Line= 3
      1452863.16      6897276.58      1453949.09      6896629.51
      1453962.02      6895576.09
#Sta/Elev= 30
  3735.9 1843.98  3743.4 1844.42    3773  1842.3  3801.8 1843.06  3864.4 1841.73
  4035.4 1840.27  4078.2 1841.06    4232 1839.06  4378.3  1839.3  4413.2 1837.98
  4561.1 1837.55  4600.3 1836.59  4662.3 1836.53  4714.9  1835.1  4853.1  1836.6
  4918.7 1836.37  4983.6 1835.56  4991.3 1833.71  5007.1  1833.5  5007.6    1833
  5015.9  1833.5  5021.5 1835.21  5037.9 1836.52  5121.5  1835.9  5161.5 1836.56
  5191.5 1834.93  5211.5 1836.28  5421.5 1837.55  5471.5  1838.7  6053.5 1840.61
#Mann= 7 ,-1 , 0
  3735.9     .07       0  3864.4    .045       0  4600.3     .07       0
  4918.7     .16       0  5007.1     .07       0  5015.9     .16       0
  5037.9     .07       0
Bank Sta=5007.1,5015.9
XS Rating Curve= 0 ,0
Exp/Cntr=0.3,0.1

Type RM Length L Ch R = 1 ,43092   ,899,899,899
BEGIN DESCRIPTION:
Sweetwater Creek Trib 41 56.4
END DESCRIPTION:
XS GIS Cut Line= 3
      1453165.74      6897500.35      1454251.08      6897038.03
      1454309.33      6895661.77
#Sta/Elev= 30
  3820.3 1840.26  4352.4 1837.66  4642.4 1836.22  4711.4    1835  4787.7 1835.91
  4811.4 1833.88    4835 1835.49  4860.3 1835.03  4872.6 1835.13  4895.6 1833.72
  4983.2 1833.12  4983.7 1832.62  4992.1 1833.12  5046.6 1835.17  5130.2 1835.87
  5144.4 1834.22  5150.2 1833.31  5180.2 1835.87  5242.3 1835.38  5270.3 1836.56
  5280.3 1834.52  5340.2 1835.43  5553.5 1836.16  5627.1 1836.52  5760.7 1837.75
  5800.7 1839.35  5859.9 1837.97  5896.6  1838.4  6002.9 1838.56  6377.5 1840.29
#Mann= 16 ,-1 , 0
  3820.3     .07       0  4352.4    .045       0  4642.4    .045       0
  4860.3     .07       0  4872.6     .16       0  4983.2     .07       0
  4992.1     .16       0  5046.6     .07       0  5144.4     .16       0
  5242.3     .07       0  5340.2    .035       0  5553.5     .07       0
  5627.1    .035       0  5859.9     .07       0  5896.6    .035       0
  6002.9     .07       0
Bank Sta=4983.2,4992.1
XS Rating Curve= 0 ,0
Exp/Cntr=0.3,0.1

Type RM Length L Ch R = 1 ,42193   ,483,483,483
BEGIN DESCRIPTION:
Sweetwater Creek Trib 41 56.3
END DESCRIPTION:
XS GIS Cut Line= 3
      1453827.04      6898209.91      1454512.69      6897744.48
      1454802.75       6896082.6
#Sta/Elev= 30
  4171.3  1836.5    4369 1835.44  4415.8 1835.78  4510.2 1834.83  4574.5 1834.97
  4603.9 1834.17  4769.1  1833.4  4869.8 1833.68  4963.8 1832.58  5199.4 1833.93
  5220.9 1833.32  5534.4 1833.72  5615.6 1832.87  5696.9 1834.16  5702.5 1831.17
    5703 1830.67  5711.5 1831.17  5736.4 1834.48  5778.1 1835.14    5801 1834.36
  5972.3    1834  6058.8 1834.65  6133.4 1835.64  6172.6 1835.11  6381.1 1836.43
  6427.7 1838.01    6448 1837.12  6518.8 1837.24  6606.1 1837.55    6687 1838.14
#Mann= 10 ,-1 , 0
  4171.3     .07       0    4369    .035       0  4510.2     .07       0
  5702.5     .07       0  5711.5     .07       0  5972.3    .035       0
  6058.8     .07       0  6172.6    .035       0  6518.8     .07       0
  6606.1    .035       0
Bank Sta=5702.5,5711.5
XS Rating Curve= 0 ,0
Exp/Cntr=0.3,0.1

Type RM Length L Ch R = 1 ,41710   ,190,190,190
BEGIN DESCRIPTION:
Sweetwater Creek Trib 41 56.2
END DESCRIPTION:
XS GIS Cut Line= 3
      1454615.86      6899047.56      1454906.74      6897983.81
      1455176.22      6896945.31
#Sta/Elev= 30
  3897.2 1837.33  4166.3 1834.74    4187 1835.19  4219.8 1833.82  4301.1 1834.57
  4373.6 1833.28  4425.5 1833.59  4653.5 1831.19  4704.6 1832.24  4709.8  1831.4
  4744.3 1832.82  4749.5 1831.58  4767.6 1832.21    4784 1830.93  4818.4 1830.53
  4818.9 1830.03  4829.1 1830.53  5209.8 1832.34  5264.3  1830.9  5290.9 1832.86
  5326.3 1832.95  5346.9 1831.17  5357.3 1832.34  5377.9 1832.75  5615.5 1832.97
  5677.5 1831.97  5691.4 1832.93  5832.5 1832.79  5997.8 1834.61  6072.9 1833.82
#Mann= 3 ,-1 , 0
  3897.2    .035       0  4818.4    .035       0  4829.1    .035       0
Bank Sta=4818.4,4829.1
XS Rating Curve= 0 ,0
Exp/Cntr=0.3,0.1

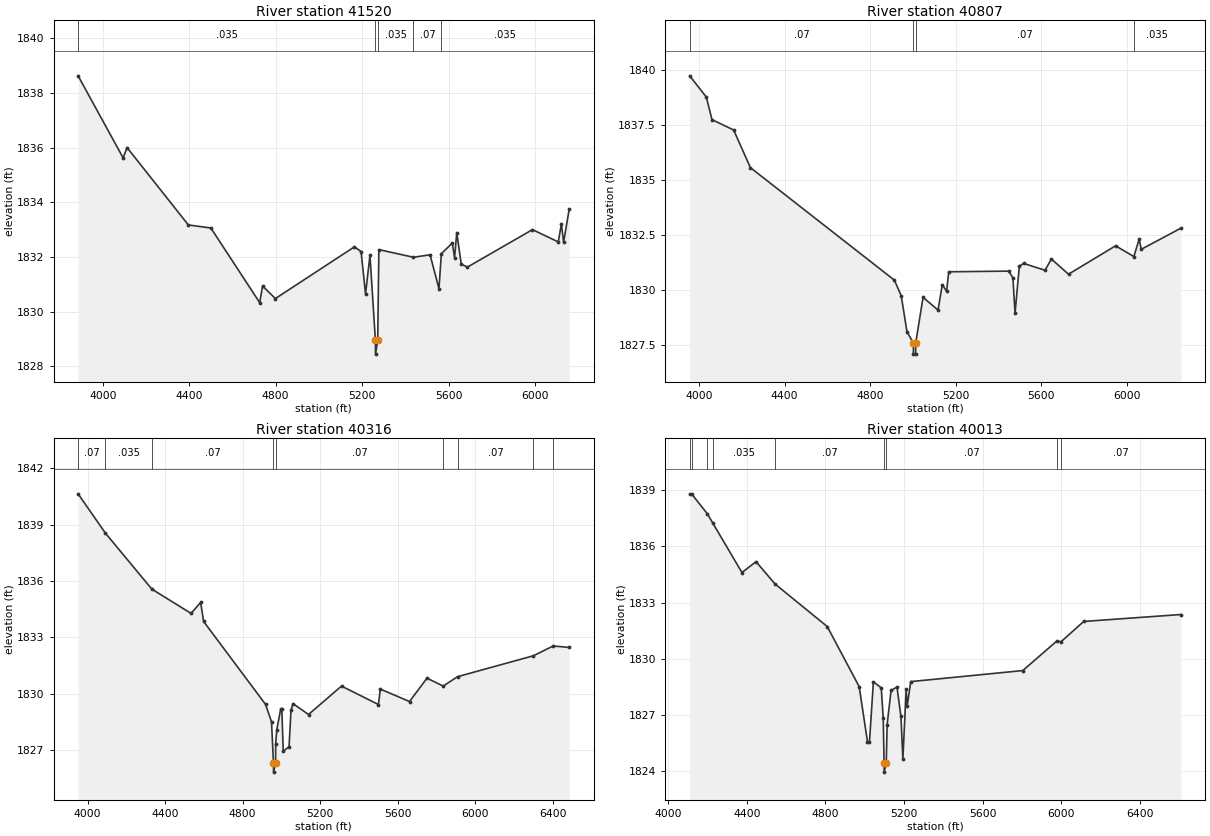
Type RM Length L Ch R = 1 ,41520   ,713,713,713
BEGIN DESCRIPTION:
Sweetwater Creek Trib 41 56.1
END DESCRIPTION:
XS GIS Cut Line= 3
      1454766.68      6899128.24      1455075.09      6898057.78
      1455351.84      6896932.52
#Sta/Elev= 30
    3886 1838.62  4094.4 1835.62  4112.4    1836  4396.2 1833.17  4500.2 1833.06
  4726.4 1830.33  4739.6 1830.94  4798.9 1830.48  5164.5 1832.37  5195.4  1832.2
    5216 1830.65  5236.6 1832.06  5261.7 1828.95  5262.2 1828.45  5272.4 1828.95
  5277.8 1832.27  5437.6 1831.99  5514.7 1832.08  5555.9 1830.84  5566.9 1832.12
  5617.7 1832.51    5628 1831.97  5638.3 1832.89  5658.8 1831.74  5687.5 1831.63
  5988.6    1833    6108 1832.55  6122.3 1833.21  6132.6 1832.54  6158.8 1833.76
#Mann= 5 ,-1 , 0
    3886    .035       0  5261.7    .035       0  5272.4    .035       0
  5437.6     .07       0  5566.9    .035       0
Bank Sta=5261.7,5272.4
XS Rating Curve= 0 ,0
Exp/Cntr=0.3,0.1

Type RM Length L Ch R = 1 ,40807   ,491,491,491
BEGIN DESCRIPTION:
Sweetwater Creek Trib 41 56.0
END DESCRIPTION:
XS GIS Cut Line= 3
      1455216.55      6899248.06      1455538.34       6898255.1
      1455537.43       6897002.9
#Sta/Elev= 30
  3956.2 1839.73  4033.7 1838.77  4060.4 1837.74  4161.6 1837.27  4240.1 1835.56
  4913.1 1830.45  4945.1 1829.74  4971.8 1828.11  5001.7 1827.59  5002.2 1827.09
  5012.1 1827.09  5012.6 1827.59  5047.1 1829.67  5117.1 1829.09  5137.1 1830.25
  5157.1 1829.94  5167.1 1830.83  5447.1 1830.86  5467.1 1830.56  5477.1 1828.95
  5497.1 1831.08  5517.1 1831.21  5617.1  1830.9  5647.1 1831.41  5727.1 1830.72
  5947.1 1832.01  6032.5 1831.52  6057.1 1832.31  6067.1 1831.85  6252.2 1832.81
#Mann= 4 ,-1 , 0
  3956.2     .07       0  5001.7     .07       0  5012.6     .07       0
  6032.5    .035       0
Bank Sta=5001.7,5012.6
XS Rating Curve= 0 ,0
Exp/Cntr=0.3,0.1

Type RM Length L Ch R = 1 ,40316   ,303,303,303
BEGIN DESCRIPTION:
Sweetwater Creek Trib 41 55.0
END DESCRIPTION:
XS GIS Cut Line= 3
      1455377.56       6899348.7        1455915.      6898447.72
      1455808.07      6896965.57
#Sta/Elev= 30
  3950.9 1840.63    4092 1838.54  4331.5 1835.57  4533.9 1834.28  4583.3 1834.86
  4598.9 1833.85  4918.2 1829.45  4949.2 1828.52  4959.2 1826.35  4959.7 1825.85
  4970.2 1826.35  4970.6 1827.37  4976.5 1828.11  4996.9 1829.21  5002.4 1829.21
  5009.7 1826.95  5039.8 1827.21  5049.8 1829.14  5059.9 1829.49  5140.1 1828.91
  5310.5 1830.42    5501 1829.44    5511 1830.26  5661.4  1829.6  5751.7 1830.84
  5835.2 1830.42  5909.5 1830.92  6300.9 1832.03  6403.3 1832.55    6486 1832.47
#Mann= 9 ,-1 , 0
  3950.9     .07       0    4092    .035       0  4331.5     .07       0
  4959.2     .07       0  4970.2     .07       0  5835.2    .035       0
  5909.5     .07       0  6300.9    .035       0  6403.3     .07       0
Bank Sta=4959.2,4970.2
XS Rating Curve= 0 ,0
Exp/Cntr=0.3,0.1

Type RM Length L Ch R = 1 ,40013   ,0,0,0
BEGIN DESCRIPTION:
Sweetwater Creek Trib 41 42.0
END DESCRIPTION:
XS GIS Cut Line= 3
      1455562.19      6899349.96      1456128.33      6898662.33
      1456065.41      6897054.06
#Sta/Elev= 30
  4109.3 1838.81  4119.3  1838.8    4199 1837.75  4226.3 1837.26  4375.3 1834.61
  4447.1 1835.19  4543.6    1834  4809.3 1831.73  4972.2 1828.52  5014.3 1825.58
  5024.4 1825.58  5044.4 1828.77  5084.4 1828.46  5094.4 1826.85  5098.9 1824.46
  5099.4 1823.96  5109.9 1824.46  5114.4  1826.5  5134.4 1828.32  5164.5  1828.5
  5184.5 1826.94  5194.5 1824.66  5211.3 1828.39  5216.3 1827.48  5234.5 1828.79
  5804.9 1829.38  5977.5 1830.95  5999.7 1830.92  6115.2    1832  6609.5 1832.37
#Mann= 9 ,-1 , 0
  4109.3     .07       0  4119.3    .035       0    4199     .07       0
  4226.3    .035       0  4543.6     .07       0  5098.9     .07       0
  5109.9     .07       0  5977.5    .035       0  5999.7     .07       0
Bank Sta=5098.9,5109.9
XS Rating Curve= 0 ,0
Exp/Cntr=0.3,0.1

Chan Stop Cuts=-1
Use User Specified Reach Order=0
Composite Channel Slope=5