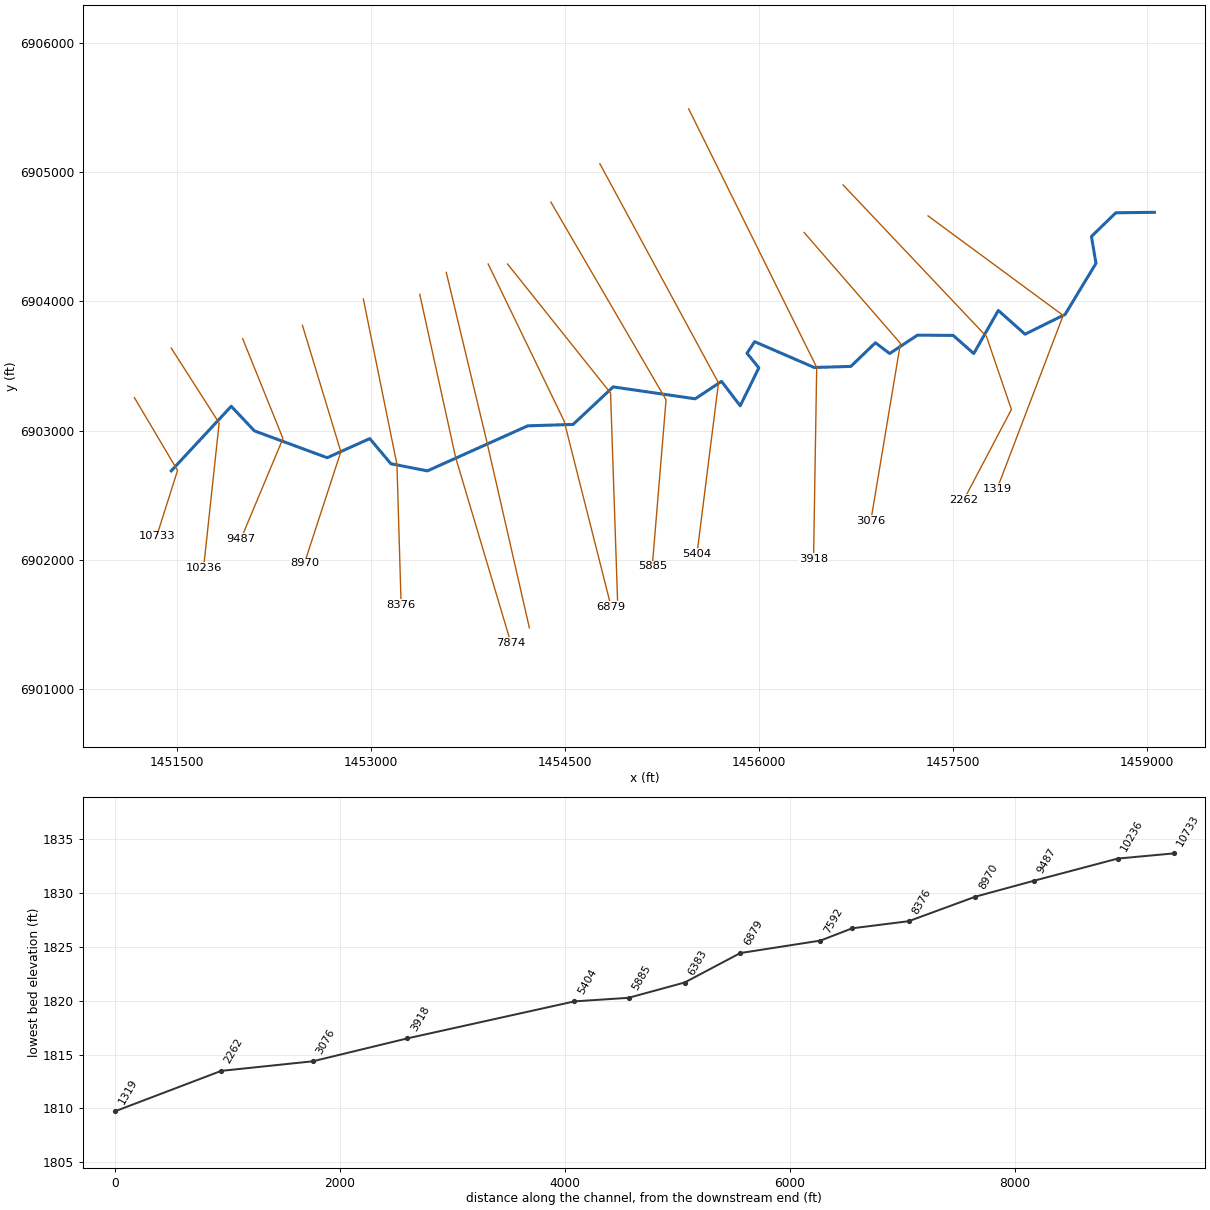
--- Sweetwater Creek Trib 41T2.prj (project) ---

Proj Title=Sweetwater Creek Trib 41T2 Base Level Engineering
Current Plan=p01
Default Exp/Contr=0.3,0.1
English Units
Geom File=g01
Flow File=f01
Plan File=p01
BEGIN DESCRIPTION:
Sweetwater Creek Trib 41T2
END DESCRIPTION:

--- Sweetwater Creek Trib 41T2.p01 (plan) ---

Plan Title=Multiple Run
Short Identifier=Multiple
Geom File=g01
Flow File=f01
Subcritical Flow
K Sum by GR= 0
Std Step Tol= 0.01
Critical Tol= 0.01
Num of Std Step Trials= 20
Max Error Tol= 0.3
Flow Tol Ratio= 0.001
Split Flow NTrial= 30
Split Flow Tol= 0.02
Split Flow Ratio= 0.02
Log Output Level= 0
Friction Slope Method= 1
Unsteady Friction Slope Method= 2
Unsteady Bridges Friction Slope Method= 1
Parabolic Critical Depth
Global Vel Dist=  1 , 1 , 1
Global Log Level= 0
CheckData=True
Encroach Param= -1, 0, 0, 0
BEGIN DESCRIPTION:
Multiple Run
END DESCRIPTION:

--- Sweetwater Creek Trib 41T2.f01 (steady flow) ---

Flow Title=Multiple
Number of Profiles=7
Profile Names=10-year,25-year,50-year,1pct_min,100-year,1pct_plu,500-year
River Rch & RM= Sweetwater Creek,Reach-1,10733
     212     289     351     212     423     843     621
River Rch & RM= Sweetwater Creek,Reach-1,8376
     316     438     537     328     654    1304     979
River Rch & RM= Sweetwater Creek,Reach-1,2262
     404     566     700     430     857    1710    1301
Boundary for River Rch & Prof#=Sweetwater Creek,Reach-1,1
Up Type=0
Dn Type=3
Dn Slope=0.005
Boundary for River Rch & Prof#=Sweetwater Creek,Reach-1,2
Up Type=0
Dn Type=3
Dn Slope=0.005
Boundary for River Rch & Prof#=Sweetwater Creek,Reach-1,3
Up Type=0
Dn Type=3
Dn Slope=0.005
Boundary for River Rch & Prof#=Sweetwater Creek,Reach-1,4
Up Type=0
Dn Type=3
Dn Slope=0.005
Boundary for River Rch & Prof#=Sweetwater Creek,Reach-1,5
Up Type=0
Dn Type=3
Dn Slope=0.005
Boundary for River Rch & Prof#=Sweetwater Creek,Reach-1,6
Up Type=0
Dn Type=3
Dn Slope=0.005
Boundary for River Rch & Prof#=Sweetwater Creek,Reach-1,7
Up Type=0
Dn Type=3
Dn Slope=0.005

--- Sweetwater Creek Trib 41T2.g01 (geometry) ---

Geom Title=Existing Conditions

River Reach=Sweetwater Creek,Reach-1
Reach XY= 30
      1451455.00      6902688.00      1451918.79      6903187.66
      1452098.01      6902997.17      1452660.63      6902789.74
      1452989.84      6902937.64      1453152.30      6902743.36
      1453434.83      6902687.71      1454211.04      6903036.37
      1454561.69      6903047.29      1454870.90      6903337.46
      1455505.08      6903245.36      1455708.69      6903380.35
      1455853.35      6903191.08      1455997.15      6903484.77
      1455905.70      6903597.85      1455964.58      6903687.31
      1456425.20      6903487.78      1456708.34      6903495.99
      1456898.33      6903679.03      1457008.33      6903595.62
      1457223.26      6903737.80      1457499.56      6903735.83
      1457658.35      6903595.58      1457848.40      6903928.78
      1458055.00      6903745.07      1458365.00      6903898.61
      1458603.27      6904293.62      1458568.34      6904501.30
      1458756.47      6904684.46      1459055.00      6904688.00

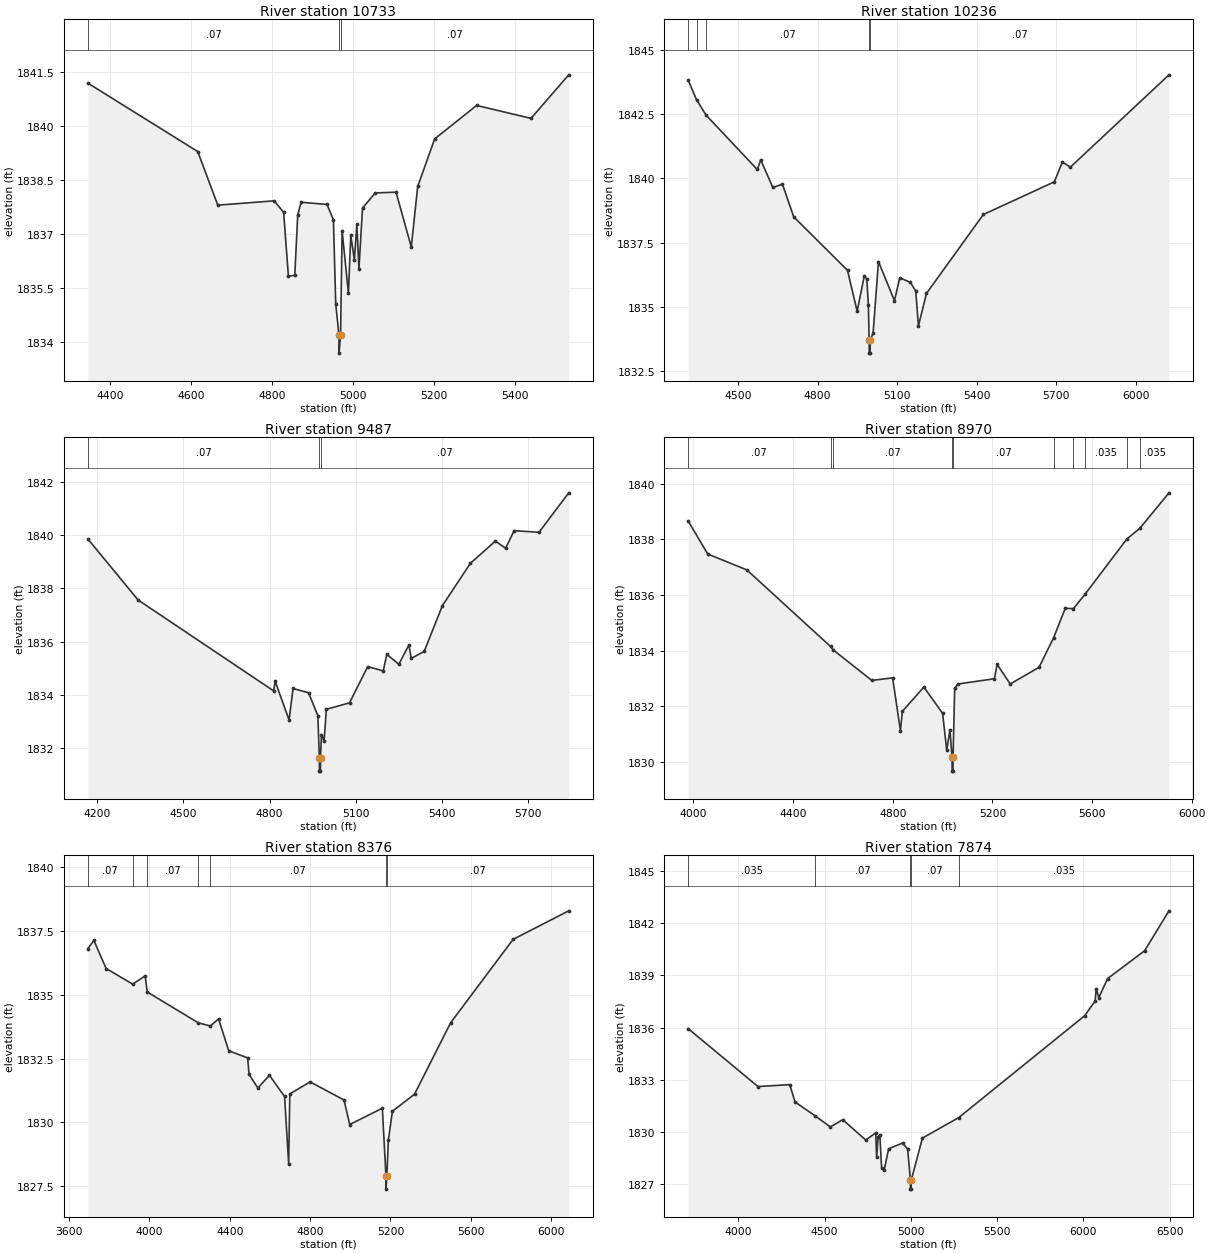
Type RM Length L Ch R = 1,10733,497,497,497
BEGIN DESCRIPTION:
Sweetwater Creek Trib 41T2 11.0
END DESCRIPTION:
XS GIS Cut Line= 3
      1451170.37      6903254.31      1451503.66      6902691.27
      1451342.54      6902182.26
#Sta/Elev= 30
  4345.7 1841.19  4617.2 1839.29  4666.8 1837.80  4806.2 1837.92  4829.5 1837.60
  4841.3 1835.83  4857.0 1835.85  4864.3 1837.52  4872.6 1837.88  4936.9 1837.82
  4952.5 1837.39  4958.3 1835.05  4966.2 1834.19  4966.4 1833.69  4970.2 1834.19
  4974.0 1837.09  4989.6 1835.35  4995.4 1836.96  5004.3 1836.28  5010.4 1837.27
  5015.6 1836.04  5024.4 1837.72  5055.9 1838.14  5107.3 1838.16  5144.9 1836.64
  5160.8 1838.32  5202.7 1839.64  5306.4 1840.57  5440.8 1840.21  5533.9 1841.42
#Mann=3,-1,0
  4345.7    0.07       0  4966.2    0.07       0  4970.2    0.07       0
Bank Sta=4966.2,4970.2
Exp/Cntr=0.3,0.1

Type RM Length L Ch R = 1,10236,749,749,749
BEGIN DESCRIPTION:
Sweetwater Creek Trib 41T2 10.0
END DESCRIPTION:
XS GIS Cut Line= 3
      1451455.00      6903638.00      1451825.38      6903057.84
      1451705.00      6901938.00
#Sta/Elev= 30
  4311.7 1843.83  4344.1 1843.05  4379.7 1842.46  4572.7 1840.35  4585.8 1840.72
  4631.5 1839.65  4667.6 1839.78  4710.2 1838.51  4913.2 1836.43  4949.6 1834.84
  4976.7 1836.22  4986.0 1836.09  4991.9 1835.10  4994.9 1833.71  4995.2 1833.21
  4998.7 1833.21  4998.9 1833.71  5009.9 1834.00  5030.0 1836.77  5090.4 1835.25
  5110.5 1836.14  5150.7 1835.96  5170.8 1835.62  5180.9 1834.27  5211.1 1835.53
  5425.9 1838.60  5693.8 1839.87  5724.0 1840.64  5754.2 1840.44  6126.3 1844.03
#Mann=5,-1,0
  4311.7    0.07       0  4344.1   0.035       0  4379.7    0.07       0
  4994.9    0.07       0  4998.9    0.07       0
Bank Sta=4994.9,4998.9
Exp/Cntr=0.3,0.1

Type RM Length L Ch R = 1,9487,517,517,517
BEGIN DESCRIPTION:
Sweetwater Creek Trib 41T2 9.0
END DESCRIPTION:
XS GIS Cut Line= 3
      1452007.28      6903710.19      1452318.69      6902938.13
      1451994.41      6902162.71
#Sta/Elev= 30
  4167.5 1839.85  4342.4 1837.56  4813.9 1834.15  4819.3 1834.51  4867.6 1833.06
  4881.5 1834.24  4935.4 1834.08  4967.8 1833.22  4973.0 1831.64  4973.2 1831.14
  4976.7 1831.14  4977.0 1831.64  4980.4 1832.51  4989.4 1832.27  4997.4 1833.46
  5077.9 1833.70  5141.1 1835.06  5195.2 1834.90  5207.7 1835.52  5249.4 1835.15
  5284.5 1835.87  5292.8 1835.37  5337.6 1835.63  5401.2 1837.35  5498.7 1838.94
  5585.5 1839.77  5621.0 1839.50  5650.5 1840.16  5737.2 1840.10  5840.5 1841.58
#Mann=3,-1,0
  4167.5    0.07       0  4973.0    0.07       0  4977.0    0.07       0
Bank Sta=4973,4977
Exp/Cntr=0.3,0.1

Type RM Length L Ch R = 1,8970,594,594,594
BEGIN DESCRIPTION:
Sweetwater Creek Trib 41T2 8.0
END DESCRIPTION:
XS GIS Cut Line= 3
      1452469.19      6903813.62      1452766.08      6902836.11
      1452484.09      6901972.06
#Sta/Elev= 30
  3978.4 1838.66  4057.4 1837.47  4214.2 1836.90  4550.1 1834.15  4560.4 1834.03
  4715.8 1832.93  4799.5 1833.02  4830.8 1831.12  4838.7 1831.82  4924.9 1832.69
  5000.0 1831.75  5016.7 1830.42  5029.6 1831.16  5038.1 1830.17  5038.3 1829.67
  5041.8 1829.67  5042.1 1830.17  5048.6 1832.64  5061.1 1832.80  5208.1 1832.99
  5218.9 1833.51  5271.5 1832.80  5387.2 1833.40  5445.7 1834.46  5492.4 1835.52
  5525.3 1835.51  5573.2 1836.04  5739.7 1838.01  5792.4 1838.40  5908.9 1839.67
#Mann=10,-1,0
  3978.4    0.07       0  4550.1   0.035       0  4560.4    0.07       0
  5038.1    0.07       0  5042.1    0.07       0  5445.7   0.035       0
  5525.3    0.07       0  5573.2   0.035       0  5739.7    0.07       0
  5792.4   0.035       0
Bank Sta=5038.1,5042.1
Exp/Cntr=0.3,0.1

Type RM Length L Ch R = 1,8376,502,502,502
BEGIN DESCRIPTION:
Sweetwater Creek Trib 41T2 7.0
END DESCRIPTION:
XS GIS Cut Line= 3
      1452940.00      6904017.42      1453199.77      6902737.51
      1453232.03      6901651.09
#Sta/Elev= 30
  3694.0 1836.81  3724.0 1837.13  3785.2 1836.03  3916.9 1835.42  3979.1 1835.74
  3989.8 1835.11  4244.5 1833.90  4303.7 1833.78  4344.5 1834.06  4395.1 1832.81
  4489.3 1832.53  4496.4 1831.88  4540.3 1831.35  4597.7 1831.85  4673.0 1831.02
  4693.4 1828.38  4699.0 1831.12  4800.3 1831.59  4968.9 1830.88  4997.2 1829.92
  5159.6 1830.56  5177.6 1827.89  5177.8 1827.39  5181.6 1827.89  5189.6 1829.31
  5209.6 1830.44  5319.7 1831.11  5499.7 1833.91  5809.9 1837.17  6086.9 1838.29
#Mann=7,-1,0
  3694.0    0.07       0  3916.9   0.035       0  3989.8    0.07       0
  4244.5   0.035       0  4303.7    0.07       0  5177.6    0.07       0
  5181.6    0.07       0
Bank Sta=5177.6,5181.6
Exp/Cntr=0.3,0.1

Type RM Length L Ch R = 1,7874,282,282,282
BEGIN DESCRIPTION:
Sweetwater Creek Trib 41T2 6.0
END DESCRIPTION:
XS GIS Cut Line= 3
      1453375.92      6904053.73      1453653.28      6902792.16
      1454080.29      6901357.88
#Sta/Elev= 30
  3708.3 1835.95  4113.5 1832.62  4297.8 1832.73  4328.1 1831.74  4444.2 1830.94
  4533.3 1830.30  4604.9 1830.72  4738.1 1829.55  4796.4 1829.96  4801.5 1828.55
  4809.7 1829.71  4820.0 1829.84  4830.2 1827.96  4845.3 1827.83  4871.2 1829.05
  4953.1 1829.38  4981.7 1829.01  4997.3 1827.23  4997.6 1826.73  5001.5 1826.73
  5001.8 1827.23  5066.9 1829.66  5277.8 1830.84  6008.0 1836.69  6068.6 1837.54
  6074.4 1838.25  6089.5 1837.73  6140.7 1838.82  6355.4 1840.42  6496.5 1842.71
#Mann=5,-1,0
  3708.3   0.035       0  4444.2    0.07       0  4997.3    0.07       0
  5001.8    0.07       0  5277.8   0.035       0
Bank Sta=4997.3,5001.8
Exp/Cntr=0.3,0.1

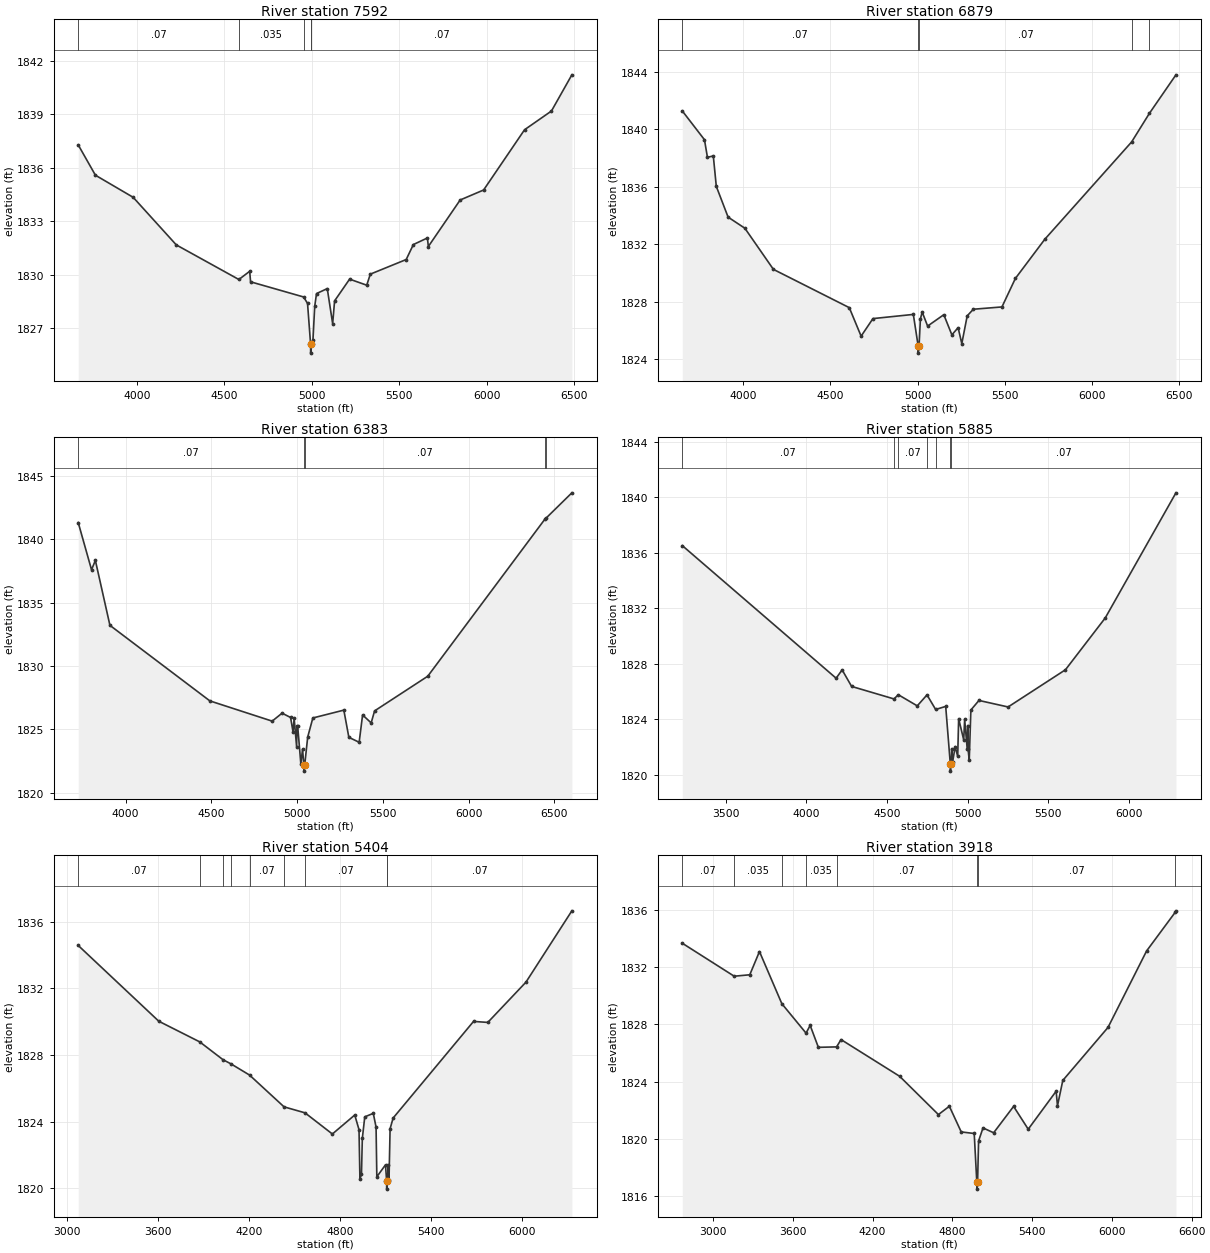
Type RM Length L Ch R = 1,7592,713,713,713
BEGIN DESCRIPTION:
Sweetwater Creek Trib 41T2 5.0
END DESCRIPTION:
XS GIS Cut Line= 3
      1453580.90      6904223.60      1453891.94      6902924.51
      1454223.16      6901474.15
#Sta/Elev= 30
  3664.2 1837.27  3762.5 1835.57  3978.4 1834.33  4225.2 1831.66  4583.0 1829.72
  4644.9 1830.18  4650.0 1829.59  4953.2 1828.74  4975.8 1828.38  4993.3 1826.09
  4993.7 1825.59  4998.3 1826.09  5006.7 1826.31  5016.9 1828.22  5027.2 1828.93
  5088.7 1829.21  5119.5 1827.24  5130.5 1828.52  5216.4 1829.74  5314.4 1829.40
  5334.9 1830.02  5540.1 1830.84  5581.1 1831.68  5661.5 1832.05  5666.7 1831.57
  5848.8 1834.18  5982.9 1834.74  6217.1 1838.12  6370.9 1839.17  6487.7 1841.20
#Mann=5,-1,0
  3664.2    0.07       0  4583.0   0.035       0  4953.2    0.07       0
  4993.3    0.07       0  4998.3    0.07       0
Bank Sta=4993.3,4998.3
Exp/Cntr=0.3,0.1

Type RM Length L Ch R = 1,6879,496,496,496
BEGIN DESCRIPTION:
Sweetwater Creek Trib 41T2 4.0
END DESCRIPTION:
XS GIS Cut Line= 3
      1453905.00      6904288.01      1454491.81      6903074.00
      1454855.00      6901638.01
#Sta/Elev= 30
  3651.6 1841.26  3778.7 1839.26  3795.7 1838.04  3829.4 1838.13  3846.5 1836.02
  3914.2 1833.88  4010.2 1833.11  4173.9 1830.25  4608.8 1827.59  4676.6 1825.61
  4744.4 1826.83  4975.9 1827.12  5003.6 1824.93  5004.0 1824.43  5008.7 1824.93
  5016.5 1826.82  5026.8 1827.28  5057.8 1826.31  5150.6 1827.10  5196.8 1825.70
  5232.6 1826.20  5253.7 1825.09  5284.7 1827.02  5319.8 1827.48  5483.9 1827.64
  5560.8 1829.62  5730.0 1832.35  6227.4 1839.11  6328.9 1841.09  6481.2 1843.77
#Mann=5,-1,0
  3651.6    0.07       0  5003.6    0.07       0  5008.7    0.07       0
  6227.4   0.035       0  6328.9    0.07       0
Bank Sta=5003.6,5008.7
Exp/Cntr=0.3,0.1

Type RM Length L Ch R = 1,6383,498,498,498
BEGIN DESCRIPTION:
Sweetwater Creek Trib 41T2 3.0
END DESCRIPTION:
XS GIS Cut Line= 3
      1454055.03      6904287.96      1454850.95      6903289.85
      1454905.00      6901687.96
#Sta/Elev= 30
  3723.4 1841.33  3801.0 1837.60  3823.4 1838.34  3908.3 1833.21  4491.2 1827.24
  4854.7 1825.64  4912.4 1826.27  4962.0 1825.93  4976.4 1824.79  4982.8 1825.87
  4997.2 1823.63  4999.2 1825.26  5003.4 1825.26  5021.9 1822.27  5031.9 1823.43
  5039.2 1822.19  5039.6 1821.69  5044.5 1822.19  5061.9 1824.38  5091.9 1825.89
  5272.7 1826.51  5302.0 1824.36  5362.1 1823.97  5382.1 1826.13  5432.1 1825.50
  5452.1 1826.45  5762.3 1829.19  6446.6 1841.62  6453.7 1841.70  6602.8 1843.68
#Mann=5,-1,0
  3723.4    0.07       0  5039.2    0.07       0  5044.5    0.07       0
  6446.6   0.035       0  6453.7    0.07       0
Bank Sta=5039.2,5044.5
Exp/Cntr=0.3,0.1

Type RM Length L Ch R = 1,5885,481,481,481
BEGIN DESCRIPTION:
Sweetwater Creek Trib 41T2 2.0
END DESCRIPTION:
XS GIS Cut Line= 3
      1454389.84      6904766.54      1455280.00      6903237.60
      1455173.41      6901951.01
#Sta/Elev= 30
  3230.8 1836.51  4184.4 1826.96  4221.7 1827.56  4280.4 1826.37  4542.8 1825.47
  4570.1 1825.77  4687.4 1824.97  4747.8 1825.76  4801.3 1824.71  4863.7 1824.93
  4892.4 1820.77  4892.8 1820.27  4897.8 1820.77  4900.9 1821.89  4907.0 1820.96
  4922.4 1822.04  4938.1 1821.33  4943.9 1824.05  4975.4 1822.52  4981.2 1824.00
  4996.9 1821.87  5000.0 1823.55  5002.3 1821.87  5009.6 1821.05  5019.7 1824.67
  5069.8 1825.36  5250.5 1824.89  5606.1 1827.57  5852.7 1831.30  6291.0 1840.31
#Mann=7,-1,0
  3230.8    0.07       0  4542.8   0.035       0  4570.1    0.07       0
  4747.8   0.035       0  4801.3    0.07       0  4892.4    0.07       0
  4897.8    0.07       0
Bank Sta=4892.4,4897.8
Exp/Cntr=0.3,0.1

Type RM Length L Ch R = 1,5404,1486,1486,1486
BEGIN DESCRIPTION:
Sweetwater Creek Trib 41T2 1.0
END DESCRIPTION:
XS GIS Cut Line= 3
      1454768.32      6905063.54      1455685.24      6903368.44
      1455519.28      6902047.42
#Sta/Elev= 30
  3072.8 1834.57  3604.8 1830.02  3875.2 1828.78  4028.7 1827.71  4081.3 1827.46
  4203.5 1826.79  4431.5 1824.88  4570.0 1824.52  4750.4 1823.25  4898.2 1824.39
  4926.3 1823.51  4932.3 1820.57  4942.5 1820.82  4948.1 1822.98  4964.3 1824.28
  5020.6 1824.49  5038.9 1823.66  5043.9 1820.68  5101.2 1821.40  5108.6 1820.44
  5109.0 1819.94  5114.1 1820.44  5119.3 1821.40  5124.3 1820.47  5131.5 1823.57
  5151.6 1824.21  5682.3 1830.01  5776.5 1829.95  6028.5 1832.37  6331.4 1836.65
#Mann=9,-1,0
  3072.8    0.07       0  3875.2   0.035       0  4028.7    0.07       0
  4081.3   0.035       0  4203.5    0.07       0  4431.5   0.035       0
  4570.0    0.07       0  5108.6    0.07       0  5114.1    0.07       0
Bank Sta=5108.6,5114.1
Exp/Cntr=0.3,0.1

Type RM Length L Ch R = 1,3918,842,842,842
BEGIN DESCRIPTION:
Sweetwater Creek Trib 41T2 1956
END DESCRIPTION:
XS GIS Cut Line= 3
      1455455.00      6905487.99      1456444.37      6903488.93
      1456420.14      6902007.22
#Sta/Elev= 30
  2769.5 1833.65  3159.7 1831.35  3277.0 1831.45  3349.8 1833.07  3518.3 1829.43
  3700.2 1827.38  3731.1 1827.92  3792.8 1826.39  3929.7 1826.42  3963.4 1826.93
  4404.0 1824.37  4695.6 1821.70  4777.9 1822.28  4867.1 1820.49  4964.8 1820.38
  4984.3 1817.00  4984.8 1816.50  4990.1 1817.00  4997.7 1819.86  5030.9 1820.77
  5110.9 1820.43  5261.0 1822.27  5371.0 1820.68  5581.0 1823.33  5591.0 1822.31
  5631.0 1824.08  5971.1 1827.78  6261.1 1833.11  6477.3 1835.82  6481.9 1835.91
#Mann=8,-1,0
  2769.5    0.07       0  3159.7   0.035       0  3518.3    0.07       0
  3700.2   0.035       0  3929.7    0.07       0  4984.3    0.07       0
  4990.1    0.07       0  6477.3   0.035       0
Bank Sta=4984.3,4990.1
Exp/Cntr=0.3,0.1

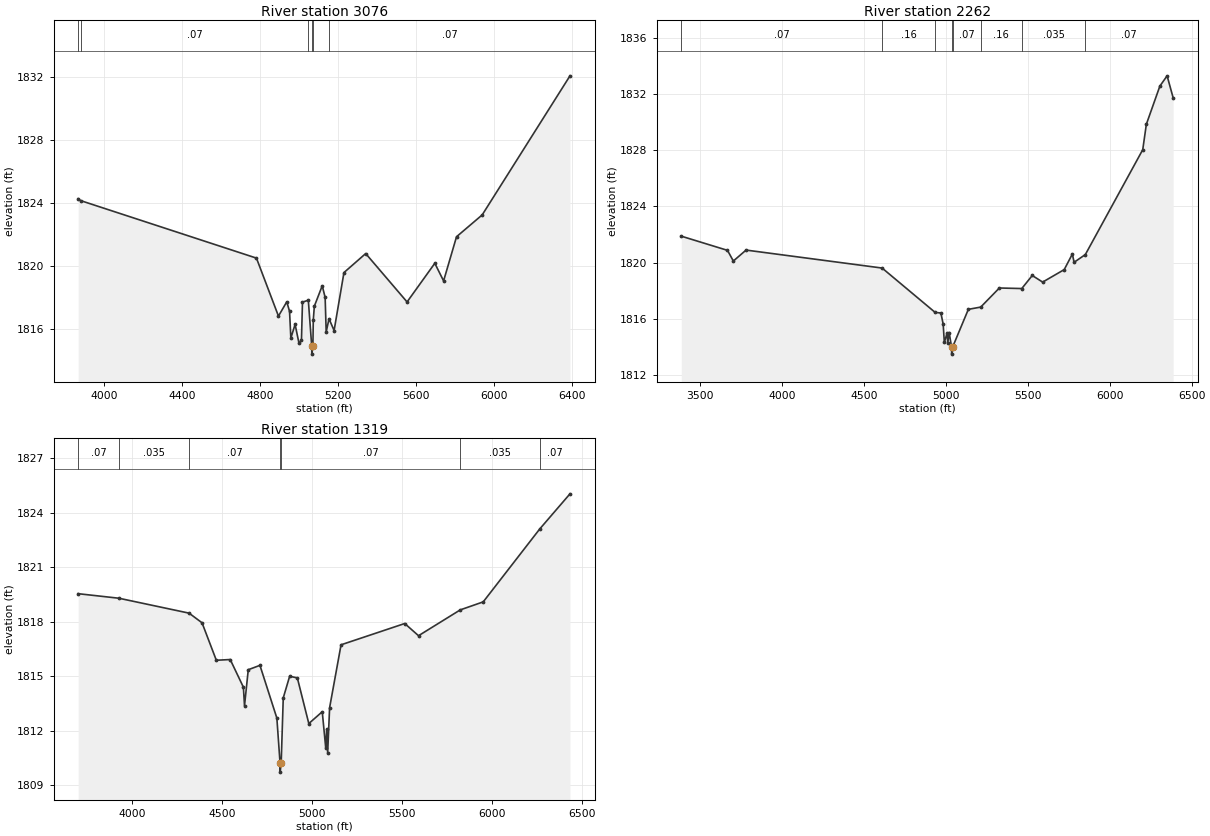
Type RM Length L Ch R = 1,3076,814,814,814
BEGIN DESCRIPTION:
Sweetwater Creek Trib 41T2 4399
END DESCRIPTION:
XS GIS Cut Line= 3
      1456347.60      6904531.57      1457091.78      6903674.32
      1456863.16      6902303.46
#Sta/Elev= 30
  3864.8 1824.26  3877.4 1824.14  4780.2 1820.48  4893.2 1816.79  4935.9 1817.70
  4950.1 1817.09  4956.8 1815.39  4978.6 1816.26  4998.6 1815.06  5011.2 1815.24
  5016.5 1817.68  5046.5 1817.80  5064.0 1814.87  5064.5 1814.37  5069.9 1814.87
  5072.0 1816.54  5077.4 1817.42  5117.9 1818.72  5132.8 1817.98  5138.2 1815.79
  5152.8 1816.62  5178.8 1815.87  5229.4 1819.56  5341.0 1820.77  5553.4 1817.69
  5695.8 1820.15  5740.9 1819.03  5807.3 1821.84  5939.1 1823.23  6389.8 1832.08
#Mann=6,-1,0
  3864.8   0.035       0  3877.4    0.07       0  5046.5    0.16       0
  5064.0    0.07       0  5069.9    0.16       0  5152.8    0.07       0
Bank Sta=5064,5069.9
Exp/Cntr=0.3,0.1

Type RM Length L Ch R = 1,2262,943,943,943
BEGIN DESCRIPTION:
Sweetwater Creek Trib 41T2 4398
END DESCRIPTION:
XS GIS Cut Line= 4
      1456648.33      6904899.88      1457756.88      6903727.35
      1457949.60      6903162.82      1457581.30      6902463.04
#Sta/Elev= 30
  3386.4 1821.88  3668.2 1820.87  3703.8 1820.11  3781.5 1820.89  4611.6 1819.61
  4935.2 1816.45  4970.1 1816.41  4984.2 1815.61  4991.1 1814.31  5007.1 1814.95
  5012.4 1814.29  5020.4 1815.02  5035.4 1813.98  5035.9 1813.48  5041.6 1813.98
  5137.7 1816.67  5213.1 1816.83  5326.9 1818.19  5463.6 1818.15  5527.6 1819.08
  5591.0 1818.61  5722.6 1819.50  5772.3 1820.61  5782.8 1820.02  5851.4 1820.57
  6201.7 1828.04  6223.7 1829.85  6306.2 1832.57  6350.3 1833.30  6387.3 1831.73
#Mann=8,-1,0
  3386.4    0.07       0  4611.6    0.16       0  4935.2    0.07       0
  5035.4    0.07       0  5041.6    0.07       0  5213.1    0.16       0
  5463.6   0.035       0  5851.4    0.07       0
Bank Sta=5035.4,5041.6
Exp/Cntr=0.3,0.1

Type RM Length L Ch R = 1,1319,0,0,0
BEGIN DESCRIPTION:
Sweetwater Creek Trib 41T2 4397
END DESCRIPTION:
XS GIS Cut Line= 3
      1457305.10      6904660.50      1458349.54      6903890.49
      1457839.54      6902550.14
#Sta/Elev= 30
  3702.4 1819.54  3928.9 1819.29  4318.6 1818.47  4390.5 1817.94  4469.9 1815.88
  4547.1 1815.92  4620.2 1814.40  4626.4 1813.38  4647.3 1815.36  4712.1 1815.60
  4806.1 1812.70  4823.8 1810.23  4824.3 1809.73  4830.1 1810.23  4841.6 1813.81
  4877.1 1815.00  4919.8 1814.91  4983.5 1812.40  5058.2 1813.05  5077.6 1811.05
  5083.0 1812.10  5088.3 1810.80  5099.0 1813.27  5162.6 1816.73  5516.2 1817.90
  5592.9 1817.23  5824.7 1818.65  5952.2 1819.09  6266.2 1823.10  6434.1 1825.03
#Mann=7,-1,0
  3702.4    0.07       0  3928.9   0.035       0  4318.6    0.07       0
  4823.8    0.07       0  4830.1    0.07       0  5824.7   0.035       0
  6266.2    0.07       0
Bank Sta=4823.8,4830.1
Exp/Cntr=0.3,0.1

Chan Stop Cuts=-1