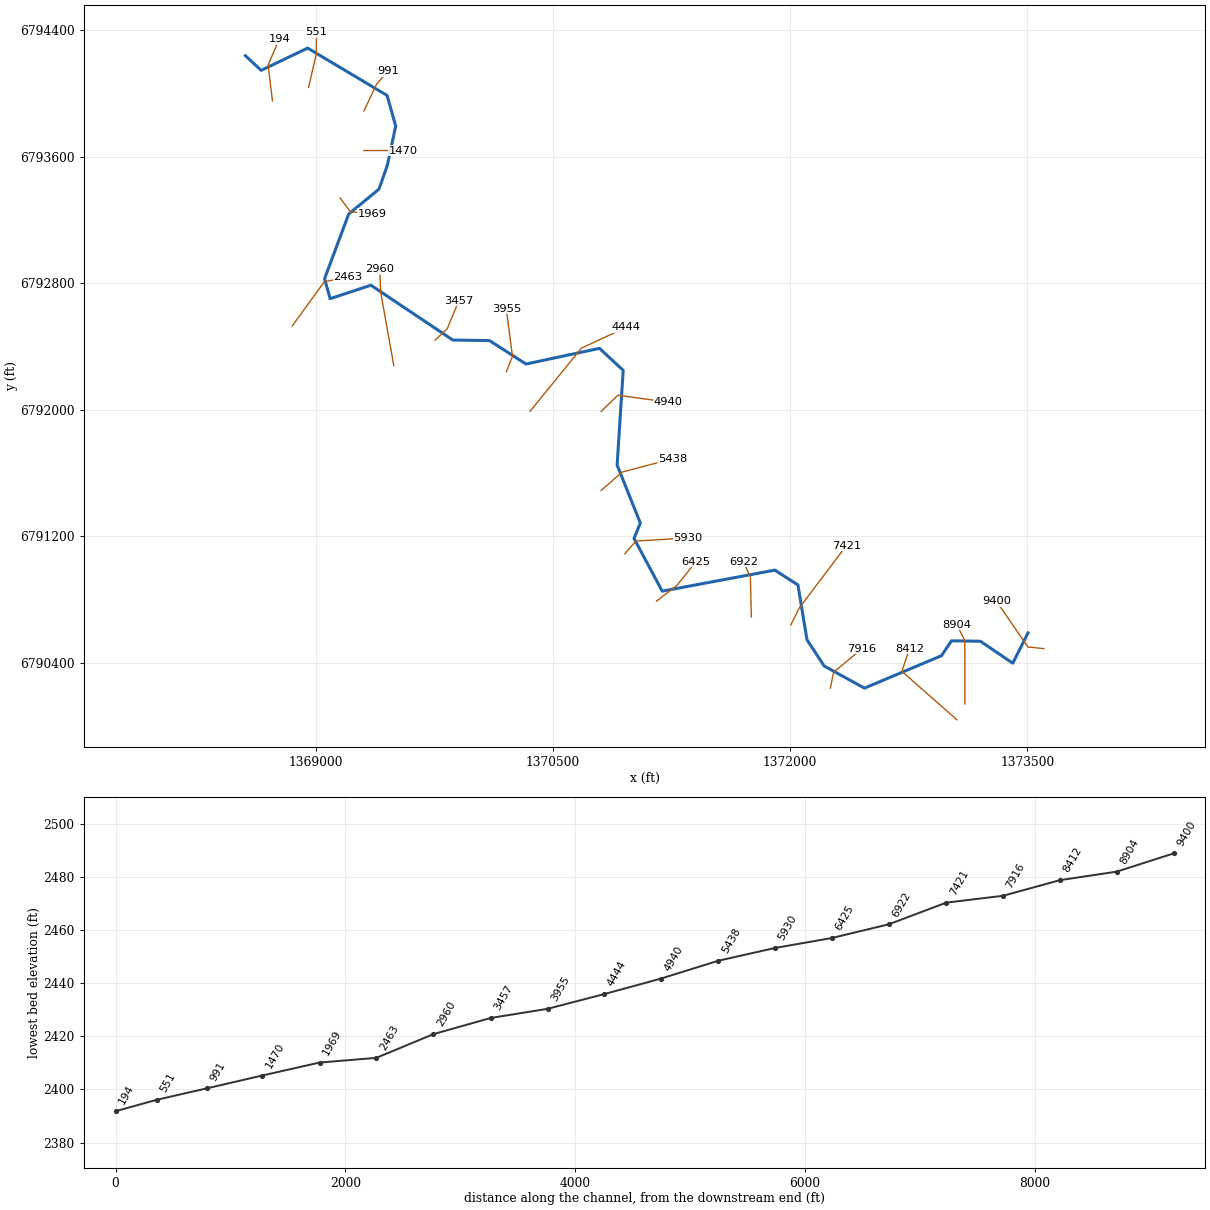
--- Sweetwater Creek Trib 5.prj (project) ---

Proj Title=Sweetwater Creek Trib 5 Base Level Engineering
Current Plan=p01
Default Exp/Contr=0.3,0.1
English Units
Geom File=g01
Flow File=f01
Plan File=p01
Y Axis Title=Elevation
X Axis Title(PF)=Main Channel Distance
X Axis Title(XS)=Station
BEGIN DESCRIPTION:
Sweetwater Creek Trib 5
END DESCRIPTION:
DSS Export Rating Curves= 0
DSS Export Rating Curve Sorted= 0
DSS Export Volume Flow Curves= 0
DXF OffsetX= 0
DXF OffsetY= 0
DXF ScaleX= 1
DXF ScaleY= 10

--- Sweetwater Creek Trib 5.p01 (plan) ---

Plan Title=Multiple Run
Short Identifier=Multiple
Geom File=g01
Flow File=f01
Subcritical Flow
K Sum by GR= 0
Std Step Tol= 0.01
Critical Tol= 0.01
Num of Std Step Trials= 20
Max Error Tol= 0.3
Flow Tol Ratio= 0.001
Split Flow NTrial= 30
Split Flow Tol= 0.02
Split Flow Ratio= 0.02
Log Output Level= 0
Friction Slope Method= 1
Unsteady Friction Slope Method= 2
Unsteady Bridges Friction Slope Method= 1
Parabolic Critical Depth
Global Vel Dist=  1 , 1 , 1
Global Log Level= 0
CheckData=True
Encroach Param= -1, 0, 0, 0
BEGIN DESCRIPTION:
Multiple Run
END DESCRIPTION:

--- Sweetwater Creek Trib 5.f01 (steady flow) ---

Flow Title=Multiple
Number of Profiles=7
Profile Names=10-year,25-year,50-year,1pct_min,100-year,1pct_plu,500-year
River Rch & RM= Sweetwater Creek,Reach-1,9400
     352     506     636     398     795    1586    1255
River Rch & RM= Sweetwater Creek,Reach-1,8904
     517     758     966     613    1222    2438    1980
River Rch & RM= Sweetwater Creek,Reach-1,3457
     620     913    1169     743    1482    2957    2414
Boundary for River Rch & Prof#=Sweetwater Creek,Reach-1,1
Up Type=0
Dn Type=3
Dn Slope=0.005
Boundary for River Rch & Prof#=Sweetwater Creek,Reach-1,2
Up Type=0
Dn Type=3
Dn Slope=0.005
Boundary for River Rch & Prof#=Sweetwater Creek,Reach-1,3
Up Type=0
Dn Type=3
Dn Slope=0.005
Boundary for River Rch & Prof#=Sweetwater Creek,Reach-1,4
Up Type=0
Dn Type=3
Dn Slope=0.005
Boundary for River Rch & Prof#=Sweetwater Creek,Reach-1,5
Up Type=0
Dn Type=3
Dn Slope=0.005
Boundary for River Rch & Prof#=Sweetwater Creek,Reach-1,6
Up Type=0
Dn Type=3
Dn Slope=0.005
Boundary for River Rch & Prof#=Sweetwater Creek,Reach-1,7
Up Type=0
Dn Type=3
Dn Slope=0.005

--- Sweetwater Creek Trib 5.g01 (geometry) ---

Geom Title=Existing Conditions

River Reach=Sweetwater Creek,Reach-1
Reach XY= 30
      1373505.00      6790588.00      1373408.42      6790395.76
      1373203.53      6790534.45      1373020.84      6790537.32
      1372957.68      6790443.40      1372470.39      6790238.07
      1372215.65      6790378.00      1372107.07      6790543.86
      1372049.64      6790890.70      1371903.42      6790984.33
      1371191.29      6790851.45      1371013.07      6791184.69
      1371053.14      6791281.87      1370906.22      6791648.50
      1370944.57      6792247.79      1370794.57      6792386.95
      1370329.92      6792287.76      1370099.14      6792435.94
      1369866.83      6792439.64      1369348.88      6792786.24
      1369091.27      6792701.16      1369056.10      6792827.44
      1369208.61      6793236.50      1369399.74      6793393.47
      1369452.73      6793543.94      1369505.81      6793793.03
      1369451.39      6793986.52      1368949.03      6794285.86
      1368654.91      6794145.19      1368555.00      6794238.00

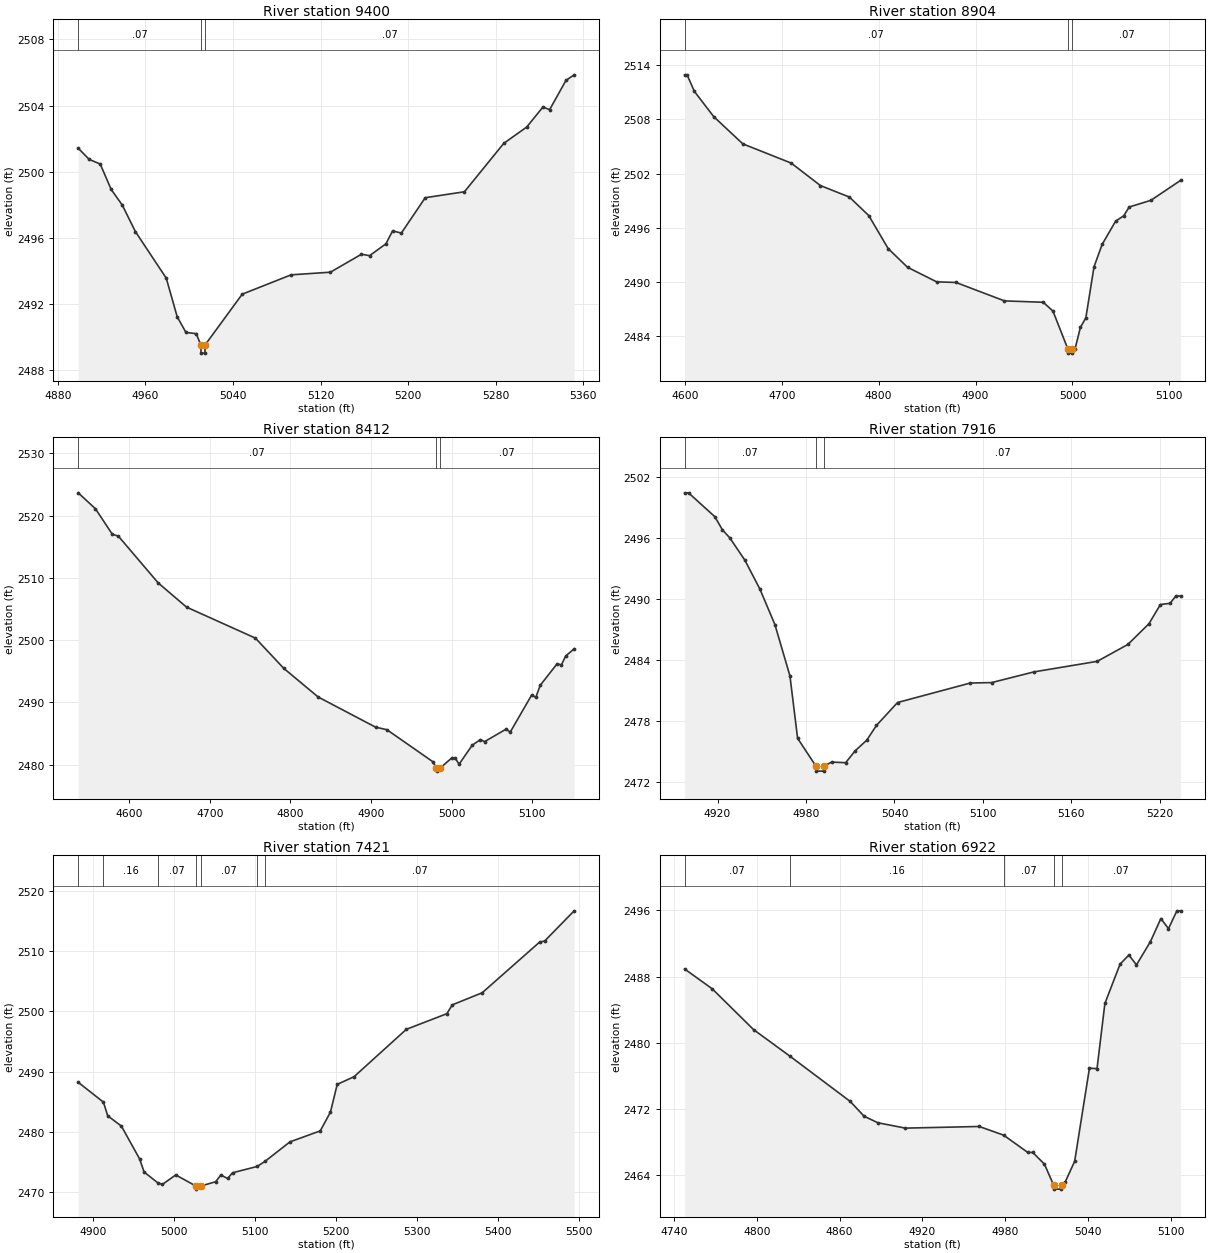
Type RM Length L Ch R = 1,9400,496,496,496
BEGIN DESCRIPTION:
Sweetwater Creek Trib 5 18.0
END DESCRIPTION:
XS GIS Cut Line= 3
      1373604.96      6790488.00      1373504.19      6790498.32
      1373304.97      6790788.04
#Sta/Elev= 30
  4898.7 2501.42  4908.7 2500.74  4918.8 2500.46  4928.8 2498.92  4938.9 2497.98
  4950.9 2496.37  4979.1 2493.55  4989.1 2491.21  4997.1 2490.26  5006.5 2490.19
  5010.6 2489.51  5010.9 2489.01  5014.4 2489.01  5014.6 2489.51  5048.5 2492.58
  5093.1 2493.75  5129.0 2493.91  5157.4 2495.00  5164.8 2494.91  5179.7 2495.63
  5185.8 2496.41  5193.8 2496.28  5215.6 2498.42  5251.4 2498.78  5287.3 2501.71
  5308.3 2502.70  5323.1 2503.91  5329.2 2503.75  5344.1 2505.52  5351.6 2505.86
#Mann=3,-1,0
  4898.7    0.07       0  5010.6    0.07       0  5014.6    0.07       0
Bank Sta=5010.6,5014.6
Exp/Cntr=0.3,0.1

Type RM Length L Ch R = 1,8904,492,492,492
BEGIN DESCRIPTION:
Sweetwater Creek Trib 5 17.0
END DESCRIPTION:
XS GIS Cut Line= 3
      1373105.00      6790137.99      1373104.93      6790538.19
      1373055.00      6790638.00
#Sta/Elev= 30
  4599.8 2512.93  4602.3 2512.93  4609.8 2511.10  4629.8 2508.30  4659.8 2505.29
  4709.8 2503.16  4739.8 2500.68  4769.8 2499.40  4789.8 2497.35  4809.8 2493.70
  4829.8 2491.63  4859.8 2490.02  4879.8 2489.95  4929.8 2487.91  4969.8 2487.76
  4979.8 2486.79  4995.1 2482.63  4995.4 2482.13  4999.4 2482.13  4999.8 2482.63
  5002.7 2482.63  5008.2 2484.98  5013.8 2486.03  5022.2 2491.67  5030.6 2494.16
  5044.5 2496.73  5052.9 2497.33  5058.5 2498.30  5080.9 2499.04  5111.6 2501.25
#Mann=3,-1,0
  4599.8    0.07       0  4995.1    0.07       0  4999.8    0.07       0
Bank Sta=4995.1,4999.8
Exp/Cntr=0.3,0.1

Type RM Length L Ch R = 1,8412,496,496,496
BEGIN DESCRIPTION:
Sweetwater Creek Trib 5 16.0
END DESCRIPTION:
XS GIS Cut Line= 3
      1373055.01      6790037.99      1372707.29      6790343.85
      1372754.99      6790487.96
#Sta/Elev= 30
  4536.9 2523.65  4558.3 2521.09  4579.2 2516.99  4586.7 2516.69  4636.1 2509.17
  4671.2 2505.29  4756.6 2500.31  4791.7 2495.46  4834.4 2490.85  4905.5 2486.01
  4919.7 2485.59  4976.4 2480.47  4981.0 2479.44  4981.3 2478.94  4985.7 2479.44
  5000.0 2481.05  5004.3 2481.05  5009.1 2480.05  5025.4 2483.10  5035.6 2484.01
  5040.8 2483.68  5067.3 2485.68  5072.6 2485.22  5099.0 2491.14  5104.3 2490.80
  5109.7 2492.72  5130.7 2496.19  5136.0 2496.01  5141.3 2497.43  5151.8 2498.59
#Mann=3,-1,0
  4536.9    0.07       0  4981.0    0.07       0  4985.7    0.07       0
Bank Sta=4981,4985.7
Exp/Cntr=0.3,0.1

Type RM Length L Ch R = 1,7916,495,495,495
BEGIN DESCRIPTION:
Sweetwater Creek Trib 5 15.0
END DESCRIPTION:
XS GIS Cut Line= 3
      1372254.99      6790237.96      1372275.03      6790338.28
      1372454.99      6790488.00
#Sta/Elev= 30
  4897.7 2500.42  4900.3 2500.42  4918.1 2498.08  4923.3 2496.78  4928.3 2495.99
  4938.5 2493.80  4948.7 2490.96  4958.9 2487.46  4969.1 2482.41  4974.3 2476.27
  4986.7 2473.54  4987.1 2473.04  4991.9 2473.04  4992.4 2473.54  4997.3 2473.93
  5006.9 2473.87  5013.4 2475.05  5021.2 2476.08  5027.8 2477.54  5042.1 2479.79
  5091.5 2481.71  5105.9 2481.75  5134.5 2482.80  5177.5 2483.84  5198.3 2485.50
  5212.6 2487.54  5220.4 2489.43  5226.9 2489.55  5230.9 2490.27  5234.1 2490.27
#Mann=3,-1,0
  4897.7    0.07       0  4986.7    0.07       0  4992.4    0.07       0
Bank Sta=4986.7,4992.4
Exp/Cntr=0.3,0.1

Type RM Length L Ch R = 1,7421,499,499,499
BEGIN DESCRIPTION:
Sweetwater Creek Trib 5 14.0
END DESCRIPTION:
XS GIS Cut Line= 3
      1372005.02      6790638.03      1372057.27      6790743.94
      1372355.01      6791138.01
#Sta/Elev= 30
  4881.9 2488.21  4913.0 2484.91  4918.3 2482.64  4935.2 2480.92  4957.7 2475.46
  4963.2 2473.29  4980.0 2471.50  4985.7 2471.22  5002.3 2472.80  5027.3 2470.94
  5027.8 2470.44  5033.0 2470.94  5051.6 2471.68  5057.9 2472.79  5066.2 2472.21
  5072.4 2473.16  5102.7 2474.21  5112.8 2475.10  5143.2 2478.30  5180.6 2480.13
  5193.2 2483.26  5201.5 2487.86  5222.3 2489.14  5286.8 2497.02  5336.8 2499.62
  5343.5 2501.09  5380.4 2503.10  5451.2 2511.52  5457.5 2511.71  5493.9 2516.73
#Mann=7,-1,0
  4881.9    0.07       0  4913.0    0.16       0  4980.0    0.07       0
  5027.3    0.07       0  5033.0    0.07       0  5102.7    0.16       0
  5112.8    0.07       0
Bank Sta=5027.3,5033
Exp/Cntr=0.3,0.1

Type RM Length L Ch R = 1,6922,497,497,497
BEGIN DESCRIPTION:
Sweetwater Creek Trib 5 13.0
END DESCRIPTION:
XS GIS Cut Line= 3
      1371755.00      6790688.05      1371749.05      6790940.28
      1371705.00      6791038.01
#Sta/Elev= 30
  4747.7 2488.92  4767.7 2486.52  4797.7 2481.58  4823.8 2478.40  4867.7 2472.90
  4877.7 2471.12  4887.7 2470.32  4907.7 2469.67  4961.2 2469.87  4978.9 2468.82
  4996.4 2466.73  5000.0 2466.73  5008.5 2465.31  5015.1 2462.79  5015.6 2462.29
  5020.4 2462.29  5020.9 2462.79  5023.5 2463.14  5030.4 2465.66  5041.1 2476.92
  5046.6 2476.87  5052.3 2484.75  5063.3 2489.51  5069.7 2490.61  5075.2 2489.42
  5085.3 2492.23  5092.9 2495.03  5098.4 2493.80  5104.5 2495.96  5107.2 2495.96
#Mann=5,-1,0
  4747.7    0.07       0  4823.8    0.16       0  4978.9    0.07       0
  5015.1    0.07       0  5020.9    0.07       0
Bank Sta=5015.1,5020.9
Exp/Cntr=0.3,0.1

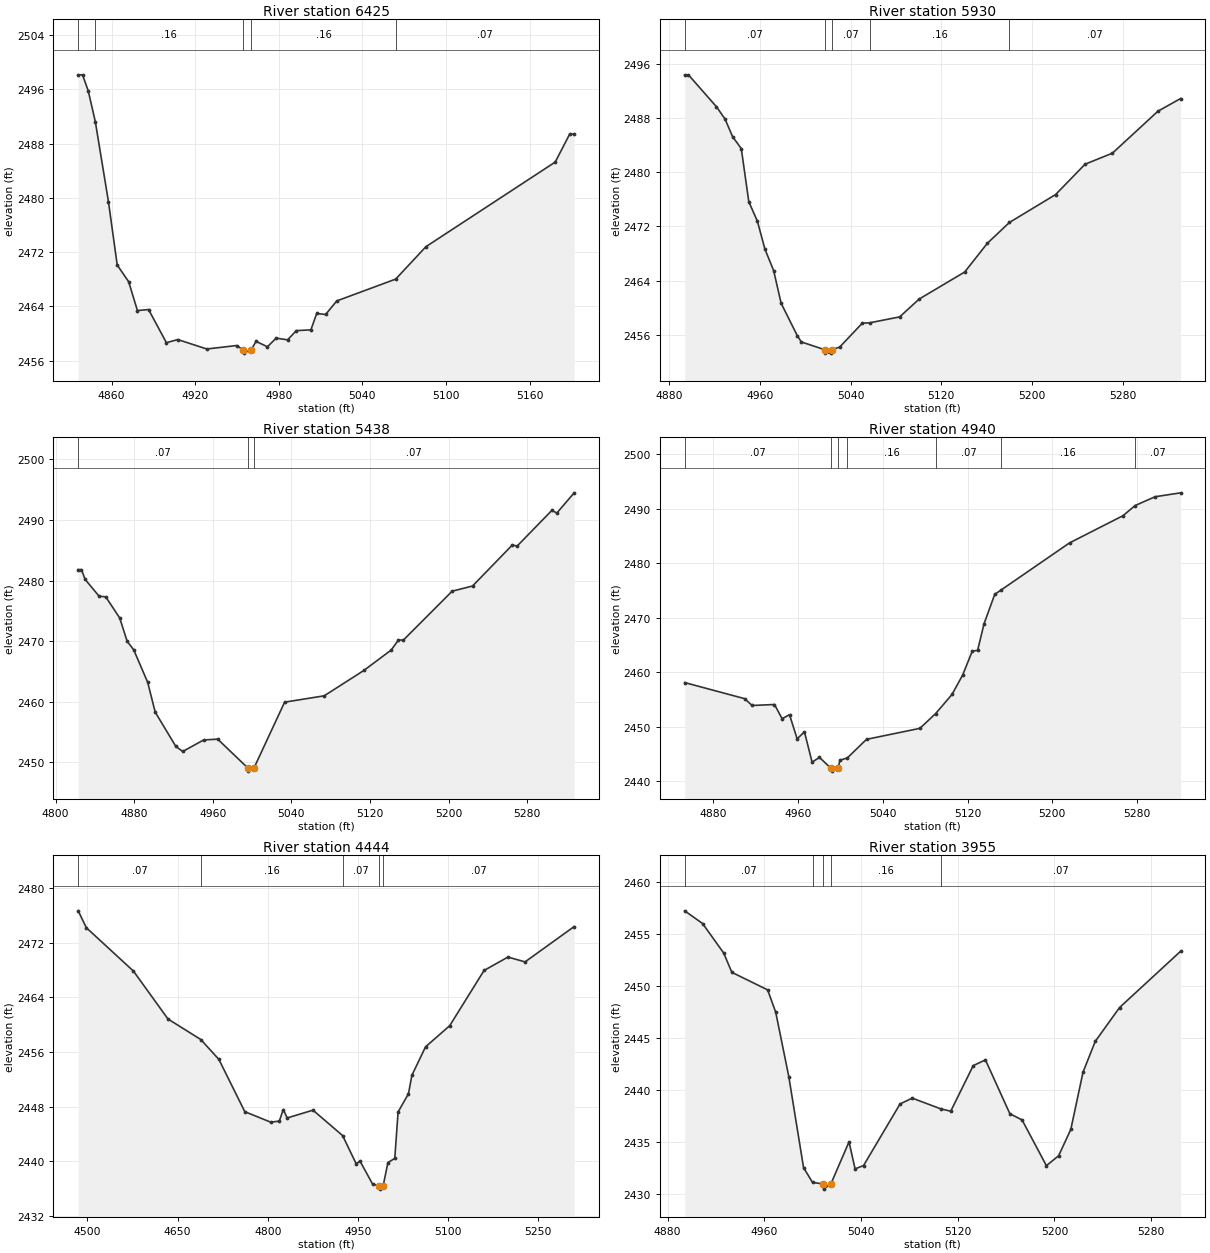
Type RM Length L Ch R = 1,6425,495,495,495
BEGIN DESCRIPTION:
Sweetwater Creek Trib 5 12.0
END DESCRIPTION:
XS GIS Cut Line= 3
      1371155.03      6790788.02      1371284.82      6790888.28
      1371405.01      6791038.01
#Sta/Elev= 30
  4836.0 2498.15  4839.1 2498.15  4843.2 2495.78  4848.3 2491.22  4857.7 2479.45
  4864.0 2470.09  4872.2 2467.64  4878.5 2463.38  4886.5 2463.53  4899.3 2458.64
  4907.5 2459.10  4928.3 2457.71  4949.7 2458.22  4954.3 2457.60  4954.8 2457.10
  4960.3 2457.60  4963.6 2458.84  4971.8 2458.04  4978.1 2459.31  4986.3 2459.06
  4992.6 2460.42  5003.0 2460.53  5007.2 2462.95  5013.6 2462.80  5021.6 2464.80
  5063.9 2468.02  5085.6 2472.80  5178.4 2485.28  5188.8 2489.41  5192.0 2489.41
#Mann=5,-1,0
  4836.0    0.07       0  4848.3    0.16       0  4954.3    0.07       0
  4960.3    0.16       0  5063.9    0.07       0
Bank Sta=4954.3,4960.3
Exp/Cntr=0.3,0.1

Type RM Length L Ch R = 1,5930,492,492,492
BEGIN DESCRIPTION:
Sweetwater Creek Trib 5 11.0
END DESCRIPTION:
XS GIS Cut Line= 3
      1370955.00      6791088.00      1371024.69      6791168.13
      1371354.99      6791188.00
#Sta/Elev= 30
  4893.8 2494.34  4897.1 2494.34  4921.8 2489.64  4929.4 2487.82  4936.0 2485.24
  4943.7 2483.47  4950.3 2475.65  4957.9 2472.77  4964.5 2468.67  4972.2 2465.51
  4978.8 2460.69  4993.0 2455.93  4996.6 2454.99  5017.3 2453.84  5017.8 2453.34
  5022.8 2453.34  5023.3 2453.84  5030.4 2454.23  5050.4 2457.76  5056.7 2457.80
  5083.3 2458.68  5100.5 2461.31  5140.6 2465.29  5160.6 2469.53  5180.0 2472.59
  5220.7 2476.70  5246.7 2481.17  5270.8 2482.80  5310.9 2488.98  5330.9 2490.85
#Mann=5,-1,0
  4893.8    0.07       0  5017.3    0.07       0  5023.3    0.07       0
  5056.7    0.16       0  5180.0    0.07       0
Bank Sta=5017.3,5023.3
Exp/Cntr=0.3,0.1

Type RM Length L Ch R = 1,5438,498,498,498
BEGIN DESCRIPTION:
Sweetwater Creek Trib 5 10.0
END DESCRIPTION:
XS GIS Cut Line= 3
      1370805.01      6791488.01      1370938.08      6791604.56
      1371254.98      6791687.99
#Sta/Elev= 30
  4823.1 2481.79  4826.4 2481.79  4830.2 2480.17  4844.4 2477.40  4851.1 2477.31
  4865.3 2473.82  4872.9 2469.97  4879.6 2468.55  4893.8 2463.19  4901.4 2458.29
  4922.3 2452.65  4929.4 2451.78  4950.7 2453.68  4965.0 2453.82  4995.8 2449.04
  4996.3 2448.54  5001.9 2449.04  5033.1 2459.92  5073.4 2460.97  5113.7 2465.15
  5141.6 2468.53  5148.9 2470.17  5154.0 2470.18  5203.6 2478.24  5224.3 2479.09
  5264.7 2485.84  5269.8 2485.70  5305.0 2491.57  5310.1 2491.14  5327.7 2494.47
#Mann=3,-1,0
  4823.1    0.07       0  4995.8    0.07       0  5001.9    0.07       0
Bank Sta=4995.8,5001.9
Exp/Cntr=0.3,0.1

Type RM Length L Ch R = 1,4940,496,496,496
BEGIN DESCRIPTION:
Sweetwater Creek Trib 5 9.0
END DESCRIPTION:
XS GIS Cut Line= 3
      1370804.97      6791987.97      1370910.75      6792090.34
      1371228.91      6792047.00
#Sta/Elev= 30
  4852.8 2458.09  4909.3 2455.14  4916.5 2453.88  4937.6 2454.06  4944.8 2451.45
  4951.8 2452.18  4959.0 2447.75  4965.9 2449.04  4973.1 2443.47  4980.1 2444.34
  4991.0 2442.32  4991.5 2441.82  4997.4 2442.32  4999.5 2443.83  5006.4 2444.25
  5024.5 2447.66  5074.9 2449.68  5089.7 2452.38  5105.2 2455.90  5115.3 2459.48
  5124.4 2463.88  5129.4 2464.00  5135.5 2468.91  5145.6 2474.30  5151.9 2475.14
  5216.2 2483.75  5266.7 2488.75  5278.1 2490.61  5297.0 2492.23  5321.1 2492.95
#Mann=7,-1,0
  4852.8    0.07       0  4991.0    0.07       0  4997.4    0.07       0
  5006.4    0.16       0  5089.7    0.07       0  5151.9    0.16       0
  5278.1    0.07       0
Bank Sta=4991,4997.4
Exp/Cntr=0.3,0.1

Type RM Length L Ch R = 1,4444,489,489,489
BEGIN DESCRIPTION:
Sweetwater Creek Trib 5 8.0
END DESCRIPTION:
XS GIS Cut Line= 3
      1370355.02      6791988.02      1370680.00      6792388.05
      1370960.87      6792519.01
#Sta/Elev= 30
  4484.6 2476.65  4498.2 2474.17  4576.5 2467.84  4634.0 2460.83  4688.6 2457.83
  4718.7 2454.92  4761.8 2447.28  4805.0 2445.74  4819.3 2445.90  4825.8 2447.59
  4832.4 2446.36  4875.3 2447.50  4924.6 2443.78  4947.2 2439.65  4953.6 2440.04
  4974.4 2436.70  4985.6 2436.45  4986.1 2435.95  4992.1 2436.45  5000.0 2439.84
  5011.4 2440.44  5016.9 2447.23  5034.2 2449.90  5039.8 2452.58  5062.6 2456.76
  5102.8 2459.85  5160.0 2467.93  5199.8 2469.89  5228.2 2469.18  5309.9 2474.35
#Mann=5,-1,0
  4484.6    0.07       0  4688.6    0.16       0  4924.6    0.07       0
  4985.6    0.07       0  4992.1    0.07       0
Bank Sta=4985.6,4992.1
Exp/Cntr=0.3,0.1

Type RM Length L Ch R = 1,3955,498,498,498
BEGIN DESCRIPTION:
Sweetwater Creek Trib 5 7.0
END DESCRIPTION:
XS GIS Cut Line= 3
      1370205.02      6792238.04      1370244.29      6792336.28
      1370205.00      6792638.03
#Sta/Elev= 30
  4894.2 2457.22  4909.0 2456.00  4926.5 2453.15  4933.2 2451.30  4962.8 2449.61
  4969.5 2447.45  4980.3 2441.26  4992.5 2432.50  4999.9 2431.08  5008.5 2430.93
  5009.0 2430.43  5015.1 2430.93  5030.1 2434.98  5035.1 2432.38  5042.1 2432.70
  5072.3 2438.63  5082.4 2439.19  5105.9 2438.16  5114.2 2437.93  5132.8 2442.32
  5142.9 2442.87  5163.1 2437.69  5173.2 2437.09  5193.3 2432.69  5203.4 2433.64
  5213.5 2436.18  5223.6 2441.69  5233.7 2444.65  5253.8 2447.91  5304.3 2453.33
#Mann=5,-1,0
  4894.2    0.07       0  4999.9    0.16       0  5008.5    0.07       0
  5015.1    0.16       0  5105.9    0.07       0
Bank Sta=5008.5,5015.1
Exp/Cntr=0.3,0.1

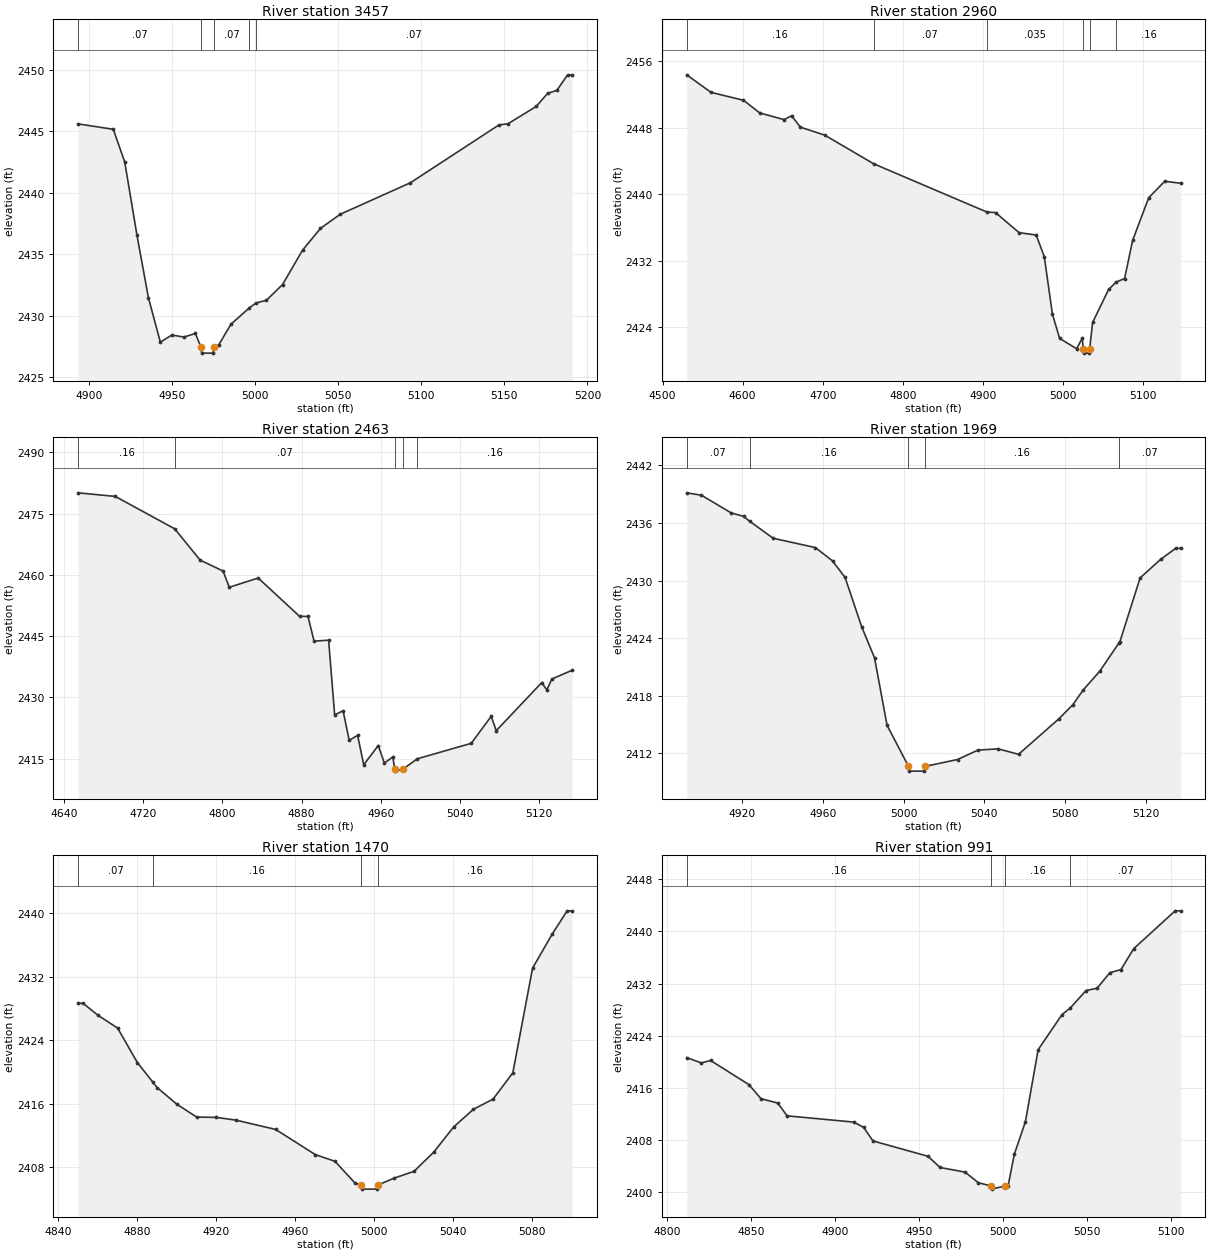
Type RM Length L Ch R = 1,3457,497,497,497
BEGIN DESCRIPTION:
Sweetwater Creek Trib 5 6.0
END DESCRIPTION:
XS GIS Cut Line= 3
      1369755.02      6792438.02      1369832.08      6792511.68
      1369905.00      6792688.00
#Sta/Elev= 30
  4893.4 2445.59  4914.6 2445.15  4921.5 2442.47  4928.8 2436.56  4935.7 2431.47
  4942.9 2427.84  4949.8 2428.42  4957.1 2428.26  4964.0 2428.55  4967.3 2427.45
  4967.8 2426.95  4974.7 2426.95  4975.2 2427.45  4978.1 2427.63  4985.4 2429.30
  4996.5 2430.63  5000.4 2431.02  5006.8 2431.25  5016.5 2432.53  5028.5 2435.32
  5039.3 2437.09  5051.2 2438.24  5093.4 2440.80  5146.8 2445.51  5152.2 2445.60
  5169.2 2447.01  5176.1 2448.08  5181.6 2448.31  5188.1 2449.58  5190.8 2449.58
#Mann=5,-1,0
  4893.4    0.07       0  4967.3    0.07       0  4975.2    0.07       0
  4996.5    0.16       0  5000.4    0.07       0
Bank Sta=4967.3,4975.2
Exp/Cntr=0.3,0.1

Type RM Length L Ch R = 1,2960,497,497,497
BEGIN DESCRIPTION:
Sweetwater Creek Trib 5 5.0
END DESCRIPTION:
XS GIS Cut Line= 3
      1369493.76      6792278.16      1369411.11      6792740.73
      1369405.00      6792888.00
#Sta/Elev= 30
  4530.1 2454.37  4560.4 2452.26  4601.0 2451.31  4621.4 2449.78  4651.8 2448.98
  4661.1 2449.44  4672.2 2448.07  4702.6 2447.11  4763.8 2443.66  4904.9 2437.87
  4916.0 2437.79  4945.4 2435.38  4966.8 2435.09  4976.9 2432.49  4987.1 2425.56
  4996.1 2422.65  5017.3 2421.41  5024.5 2422.69  5025.5 2421.38  5026.0 2420.88
  5033.1 2420.88  5033.6 2421.38  5037.3 2424.57  5057.3 2428.54  5066.8 2429.43
  5077.3 2429.86  5087.3 2434.44  5107.4 2439.58  5127.4 2441.56  5147.4 2441.32
#Mann=6,-1,0
  4530.1    0.16       0  4763.8    0.07       0  4904.9   0.035       0
  5025.5   0.035       0  5033.6   0.035       0  5066.8    0.16       0
Bank Sta=5025.5,5033.6
Exp/Cntr=0.3,0.1

Type RM Length L Ch R = 1,2463,494,494,494
BEGIN DESCRIPTION:
Sweetwater Creek Trib 5 4.0
END DESCRIPTION:
XS GIS Cut Line= 3
      1368851.19      6792528.10      1369054.39      6792808.03
      1369205.03      6792838.01
#Sta/Elev= 30
  4654.1 2480.10  4691.7 2479.22  4751.8 2471.28  4777.5 2463.61  4800.7 2460.94
  4806.9 2456.96  4836.2 2459.23  4878.0 2449.85  4886.5 2449.81  4892.7 2443.76
  4907.4 2444.00  4913.5 2425.69  4922.0 2426.72  4928.2 2419.48  4936.7 2420.67
  4942.9 2413.48  4957.6 2418.19  4963.8 2413.89  4972.3 2415.40  4974.3 2412.42
  4974.8 2411.92  4982.7 2412.42  4997.0 2414.94  5051.6 2418.73  5071.8 2425.35
  5076.9 2421.83  5122.9 2433.61  5128.0 2431.83  5133.2 2434.49  5153.6 2436.63
#Mann=5,-1,0
  4654.1    0.16       0  4751.8    0.07       0  4974.3    0.07       0
  4982.7    0.07       0  4997.0    0.16       0
Bank Sta=4974.3,4982.7
Exp/Cntr=0.3,0.1

Type RM Length L Ch R = 1,1969,499,499,499
BEGIN DESCRIPTION:
Sweetwater Creek Trib 5 3.0
END DESCRIPTION:
XS GIS Cut Line= 3
      1369155.00      6793338.00      1369218.40      6793251.30
      1369354.96      6793238.00
#Sta/Elev= 30
  4892.6 2439.13  4899.9 2438.88  4914.6 2437.04  4920.8 2436.68  4923.7 2436.18
  4935.4 2434.40  4956.3 2433.43  4964.8 2432.04  4971.0 2430.32  4979.3 2425.14
  4985.6 2421.94  4991.8 2414.92  5002.4 2410.65  5002.9 2410.15  5010.3 2410.15
  5010.8 2410.65  5026.7 2411.36  5036.8 2412.34  5046.8 2412.47  5056.9 2411.90
  5077.0 2415.62  5083.8 2417.07  5088.8 2418.57  5097.1 2420.55  5106.6 2423.49
  5107.1 2423.64  5117.1 2430.27  5127.2 2432.19  5134.7 2433.35  5137.2 2433.35
#Mann=5,-1,0
  4892.6    0.07       0  4923.7    0.16       0  5002.4    0.07       0
  5010.8    0.16       0  5106.6    0.07       0
Bank Sta=5002.4,5010.8
Exp/Cntr=0.3,0.1

Type RM Length L Ch R = 1,1470,479,479,479
BEGIN DESCRIPTION:
Sweetwater Creek Trib 5 2.0
END DESCRIPTION:
XS GIS Cut Line= 3
      1369304.97      6793638.00      1369454.67      6793638.14
      1369554.97      6793638.00
#Sta/Elev= 30
  4850.3 2428.65  4852.8 2428.65  4860.3 2427.15  4870.3 2425.53  4880.3 2421.19
  4888.2 2418.70  4890.3 2418.04  4900.3 2415.94  4910.3 2414.33  4920.3 2414.29
  4930.3 2413.94  4950.3 2412.77  4970.3 2409.61  4980.3 2408.76  4990.3 2406.06
  4993.4 2405.76  4993.9 2405.26  5001.4 2405.26  5001.9 2405.76  5010.3 2406.65
  5020.3 2407.50  5030.3 2409.92  5040.3 2413.07  5050.3 2415.30  5060.3 2416.59
  5070.3 2419.90  5080.3 2433.08  5090.3 2437.39  5097.8 2440.29  5100.3 2440.29
#Mann=4,-1,0
  4850.3    0.07       0  4888.2    0.16       0  4993.4    0.07       0
  5001.9    0.16       0
Bank Sta=4993.4,5001.9
Exp/Cntr=0.3,0.1

Type RM Length L Ch R = 1,991,440,440,440
BEGIN DESCRIPTION:
Sweetwater Creek Trib 5 1.0
END DESCRIPTION:
XS GIS Cut Line= 3
      1369304.99      6793887.97      1369385.24      6794058.42
      1369454.98      6794137.98
#Sta/Elev= 30
  4811.6 2420.64  4820.3 2419.82  4825.8 2420.20  4848.6 2416.50  4855.8 2414.34
  4865.8 2413.66  4871.4 2411.70  4911.1 2410.74  4917.0 2409.92  4922.5 2407.85
  4955.3 2405.49  4962.5 2403.77  4977.4 2403.06  4985.3 2401.43  4992.7 2400.95
  4993.2 2400.45  5001.4 2400.95  5003.0 2400.95  5006.7 2405.80  5013.3 2410.79
  5020.9 2421.86  5035.1 2427.24  5040.0 2428.25  5049.4 2430.93  5056.0 2431.29
  5063.6 2433.67  5070.2 2434.15  5077.8 2437.36  5102.5 2443.17  5105.8 2443.17
#Mann=4,-1,0
  4811.6    0.16       0  4992.7    0.07       0  5001.4    0.16       0
  5040.0    0.07       0
Bank Sta=4992.7,5001.4
Exp/Cntr=0.3,0.1

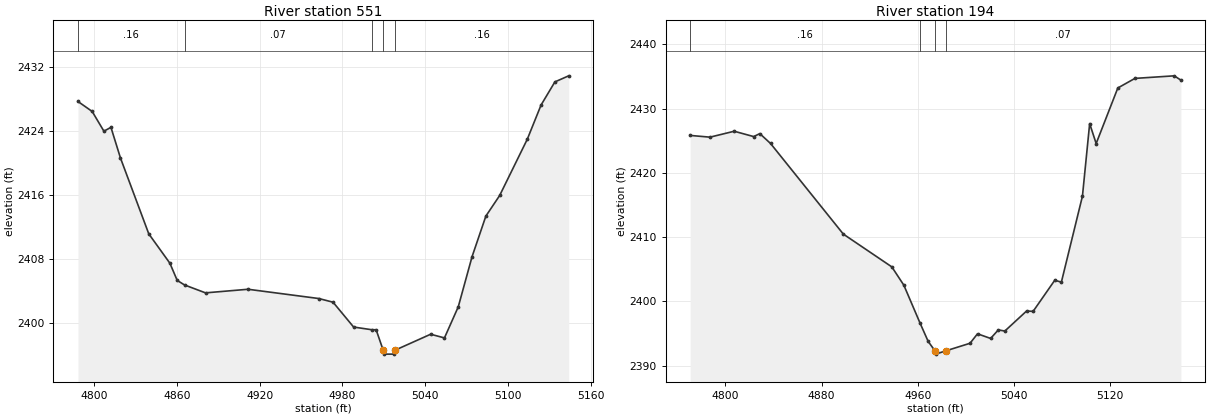
Type RM Length L Ch R = 1,551,357,357,357
BEGIN DESCRIPTION:
Sweetwater Creek Trib 5 2533
END DESCRIPTION:
XS GIS Cut Line= 3
      1368955.00      6794038.00      1369002.82      6794244.12
      1369005.00      6794388.01
#Sta/Elev= 30
  4788.4 2427.73  4798.7 2426.48  4807.2 2424.01  4812.3 2424.49  4819.2 2420.65
  4839.7 2411.16  4855.0 2407.48  4860.3 2405.33  4865.6 2404.76  4880.8 2403.77
  4911.6 2404.22  4962.9 2403.06  4973.2 2402.60  4988.1 2399.49  5001.4 2399.15
  5004.4 2399.15  5009.5 2396.60  5010.0 2396.10  5017.7 2396.10  5018.2 2396.60
  5043.9 2398.59  5053.9 2398.13  5063.9 2402.02  5073.9 2408.30  5083.9 2413.38
  5093.9 2415.96  5113.9 2423.00  5123.9 2427.29  5133.9 2430.18  5143.9 2430.94
#Mann=5,-1,0
  4788.4    0.16       0  4865.6    0.07       0  5001.4    0.16       0
  5009.5    0.07       0  5018.2    0.16       0
Bank Sta=5009.5,5018.2
Exp/Cntr=0.3,0.1

Type RM Length L Ch R = 1,194,0,0,0
BEGIN DESCRIPTION:
Sweetwater Creek Trib 5 4400
END DESCRIPTION:
XS GIS Cut Line= 3
      1368726.47      6793951.65      1368698.95      6794179.19
      1368769.95      6794343.07
#Sta/Elev= 30
  4770.8 2425.82  4787.3 2425.55  4807.4 2426.47  4823.6 2425.64  4828.7 2426.10
  4837.6 2424.57  4898.1 2410.47  4938.4 2405.37  4948.4 2402.52  4961.8 2396.65
  4968.6 2393.78  4974.3 2392.30  4974.8 2391.80  4983.1 2392.30  5003.4 2393.49
  5009.6 2394.96  5020.5 2394.24  5026.9 2395.57  5032.3 2395.39  5050.4 2398.51
  5055.8 2398.45  5073.8 2403.29  5079.3 2403.00  5096.8 2416.37  5102.8 2427.66
  5108.2 2424.56  5126.2 2433.20  5140.4 2434.69  5173.1 2435.09  5178.6 2434.42
#Mann=4,-1,0
  4770.8    0.16       0  4961.8    0.07       0  4974.3    0.07       0
  4983.1    0.07       0
Bank Sta=4974.3,4983.1
Exp/Cntr=0.3,0.1

Chan Stop Cuts=-1