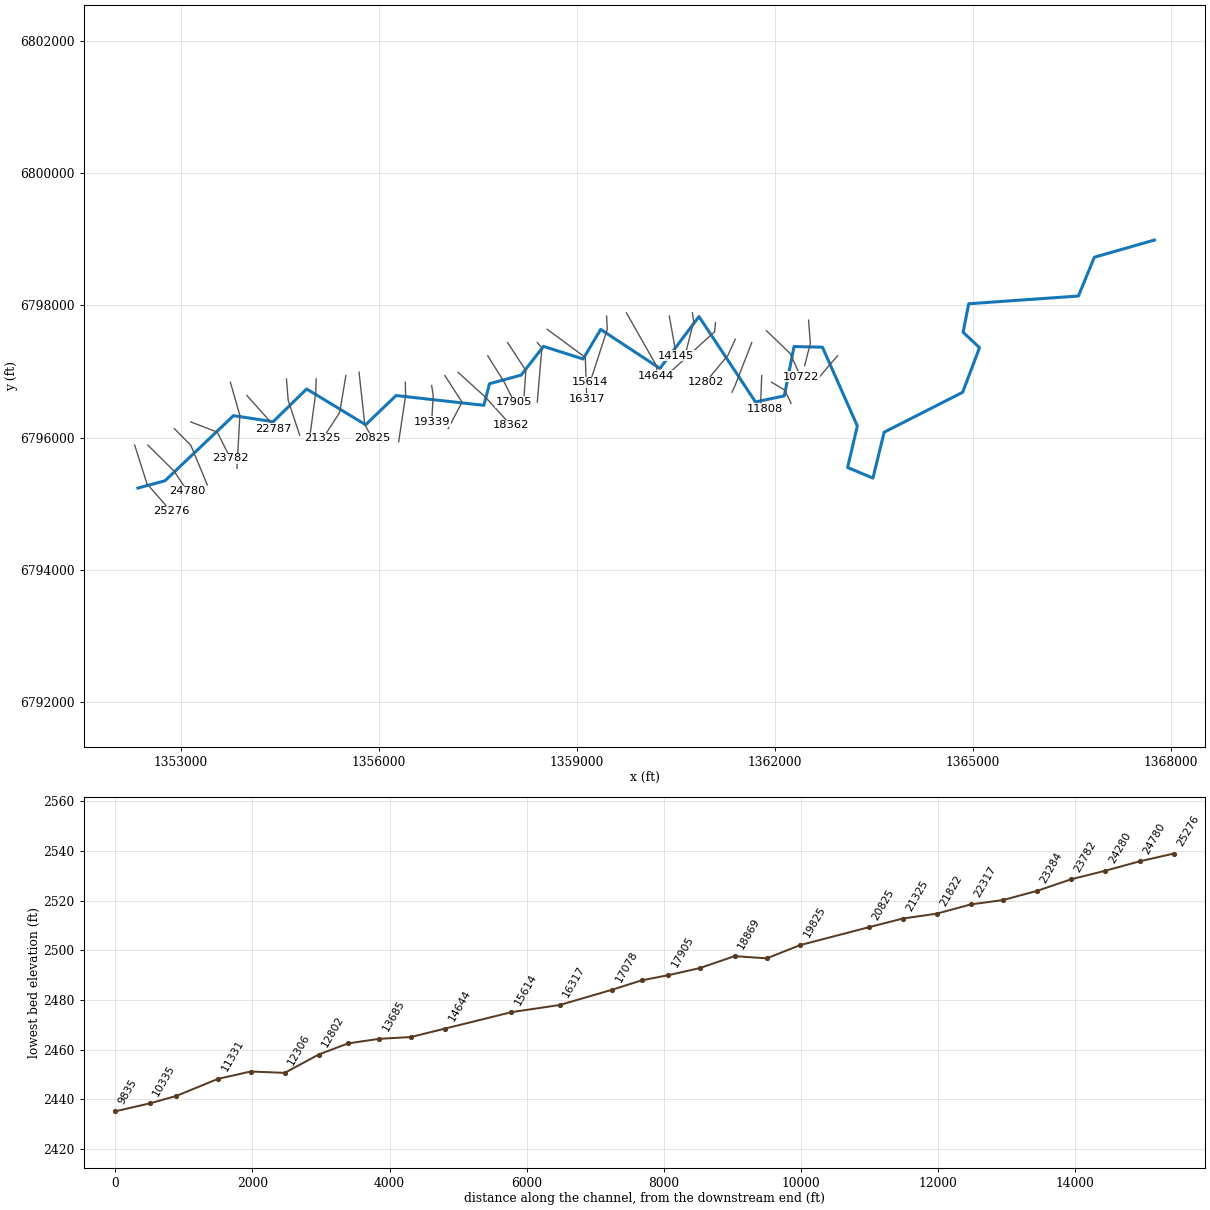
--- Sweetwater Creek Trib 6.prj (project) ---

Proj Title=Sweetwater Creek Trib 6 Base Level Engineering
Current Plan=p01
Default Exp/Contr=0.3,0.1
English Units
Geom File=g01
Flow File=f01
Plan File=p01
BEGIN DESCRIPTION:
Sweetwater Creek Trib 6
END DESCRIPTION:

--- Sweetwater Creek Trib 6.p01 (plan) ---

Plan Title=Multiple Run
Short Identifier=Multiple
Geom File=g01
Flow File=f01
Subcritical Flow
K Sum by GR= 0
Std Step Tol= 0.01
Critical Tol= 0.01
Num of Std Step Trials= 20
Max Error Tol= 0.3
Flow Tol Ratio= 0.001
Split Flow NTrial= 30
Split Flow Tol= 0.02
Split Flow Ratio= 0.02
Log Output Level= 0
Friction Slope Method= 1
Unsteady Friction Slope Method= 2
Unsteady Bridges Friction Slope Method= 1
Parabolic Critical Depth
Global Vel Dist=  1 , 1 , 1
Global Log Level= 0
CheckData=True
Encroach Param= -1, 0, 0, 0
BEGIN DESCRIPTION:
Multiple Run
END DESCRIPTION:

--- Sweetwater Creek Trib 6.f01 (steady flow) ---

Flow Title=Multiple
Number of Profiles=7
Profile Names=10-year,25-year,50-year,1pct_min,100-year,1pct_plu,500-year
River Rch & RM= Sweetwater Creek,Reach-1,25276
     349     498     624     388     774    1544    1209
River Rch & RM= Sweetwater Creek,Reach-1,18362
     427     617     778     487     973    1941    1540
River Rch & RM= Sweetwater Creek,Reach-1,15614
     552     807    1027     649    1295    2583    2084
River Rch & RM= Sweetwater Creek,Reach-1,14145
     680    1005    1289     820    1636    3264    2671
River Rch & RM= Sweetwater Creek,Reach-1,6026
     719    1066    1370     872    1741    3473    2850
River Rch & RM= Sweetwater Creek,Reach-1,2127
     920    1379    1786    1145    2285    4558    3793
Boundary for River Rch & Prof#=Sweetwater Creek,Reach-1,1
Up Type=0
Dn Type=3
Dn Slope=0.005
Boundary for River Rch & Prof#=Sweetwater Creek,Reach-1,2
Up Type=0
Dn Type=3
Dn Slope=0.005
Boundary for River Rch & Prof#=Sweetwater Creek,Reach-1,3
Up Type=0
Dn Type=3
Dn Slope=0.005
Boundary for River Rch & Prof#=Sweetwater Creek,Reach-1,4
Up Type=0
Dn Type=3
Dn Slope=0.005
Boundary for River Rch & Prof#=Sweetwater Creek,Reach-1,5
Up Type=0
Dn Type=3
Dn Slope=0.005
Boundary for River Rch & Prof#=Sweetwater Creek,Reach-1,6
Up Type=0
Dn Type=3
Dn Slope=0.005
Boundary for River Rch & Prof#=Sweetwater Creek,Reach-1,7
Up Type=0
Dn Type=3
Dn Slope=0.005

--- Sweetwater Creek Trib 6.g01 (geometry) ---

Geom Title=Existing Conditions

River Reach=Sweetwater Creek,Reach-1
Reach XY= 30
      1352355.00      6795238.00      1352764.79      6795348.52
      1353802.56      6796332.61      1354403.74      6796241.48
      1354910.63      6796736.26      1355804.67      6796195.19
      1356265.50      6796636.80      1357595.75      6796489.20
      1357680.97      6796815.35      1358161.05      6796946.16
      1358498.87      6797380.26      1359099.17      6797189.53
      1359365.51      6797636.80      1360262.02      6797046.99
      1360855.00      6797830.92      1361710.44      6796540.17
      1362147.27      6796631.50      1362294.87      6797377.66
      1362725.13      6797368.24      1363253.78      6796177.50
      1363106.71      6795548.85      1363490.31      6795388.86
      1363660.18      6796082.59      1364849.17      6796685.69
      1365105.11      6797360.69      1364856.54      6797593.83
      1364941.33      6798024.78      1366603.52      6798141.61
      1366844.94      6798727.97      1367755.00      6798988.00

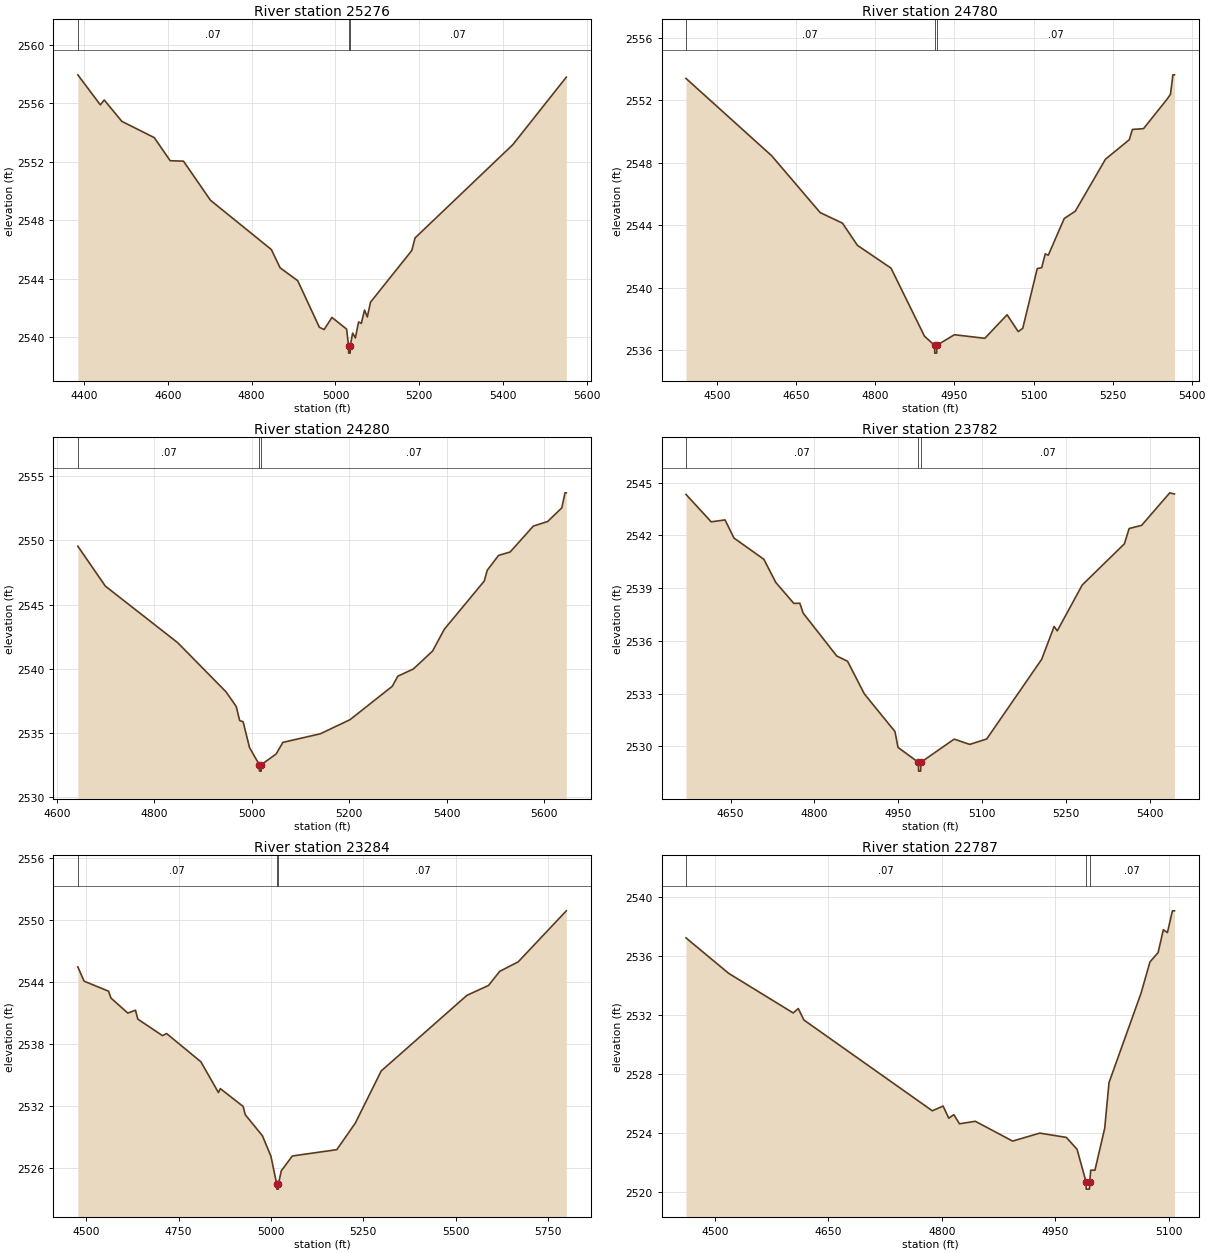
Type RM Length L Ch R = 1,25276,496,496,496
BEGIN DESCRIPTION:
Sweetwater Creek Trib 6 47.0
END DESCRIPTION:
XS GIS Cut Line= 3
      1352304.99      6795888.04      1352491.69      6795302.17
      1352854.98      6794888.03
#Sta/Elev= 30
  4385.1 2557.93  4438.7 2555.88  4448.1 2556.21  4490.1 2554.75  4567.5 2553.64
  4605.5 2552.06  4637.2 2552.03  4701.6 2549.36  4846.9 2545.99  4867.9 2544.74
  4909.9 2543.86  4961.5 2540.68  4972.9 2540.52  4991.5 2541.35  5026.6 2540.55
  5031.2 2539.41  5031.5 2538.91  5035.0 2538.91  5035.3 2539.41  5040.9 2540.28
  5047.5 2539.95  5055.1 2541.04  5061.7 2540.94  5069.3 2541.85  5076.0 2541.38
  5083.6 2542.39  5182.3 2545.93  5189.8 2546.78  5423.3 2553.16  5550.9 2557.77
#Mann=3,-1,0
  4385.1    0.07       0  5031.2    0.07       0  5035.3    0.07       0
Bank Sta=5031.2,5035.3
Exp/Cntr=0.3,0.1

Type RM Length L Ch R = 1,24780,500,500,500
BEGIN DESCRIPTION:
Sweetwater Creek Trib 6 46.0
END DESCRIPTION:
XS GIS Cut Line= 3
      1352505.03      6795887.97      1352902.31      6795494.43
      1353105.00      6795188.00
#Sta/Elev= 30
  4440.8 2553.41  4603.4 2548.45  4695.3 2544.81  4737.7 2544.13  4766.0 2542.71
  4829.7 2541.25  4893.3 2536.88  4912.4 2536.30  4912.7 2535.80  4916.3 2535.80
  4916.6 2536.30  4949.9 2536.98  5007.7 2536.75  5049.9 2538.26  5071.0 2537.18
  5079.6 2537.39  5107.1 2541.22  5115.6 2541.28  5122.2 2542.16  5128.1 2542.08
  5158.3 2544.43  5179.3 2544.90  5236.5 2548.23  5281.7 2549.48  5287.6 2550.14
  5308.7 2550.19  5353.9 2552.10  5359.9 2552.40  5364.4 2553.64  5367.4 2553.64
#Mann=3,-1,0
  4440.8    0.07       0  4912.4    0.07       0  4916.6    0.07       0
Bank Sta=4912.4,4916.6
Exp/Cntr=0.3,0.1

Type RM Length L Ch R = 1,24280,498,498,498
BEGIN DESCRIPTION:
Sweetwater Creek Trib 6 45.0
END DESCRIPTION:
XS GIS Cut Line= 3
      1352904.99      6796138.01      1353156.42      6795884.15
      1353405.00      6795288.00
#Sta/Elev= 30
  4642.7 2549.55  4699.2 2546.44  4847.8 2542.03  4946.8 2538.21  4968.0 2537.06
  4975.1 2535.96  4982.1 2535.87  4995.4 2533.85  5015.4 2532.52  5015.7 2532.02
  5019.3 2532.02  5019.6 2532.52  5050.0 2533.36  5063.8 2534.26  5140.7 2534.93
  5201.7 2536.03  5288.4 2538.63  5299.9 2539.42  5331.7 2539.98  5371.3 2541.38
  5395.2 2543.07  5477.5 2546.84  5483.4 2547.67  5506.7 2548.83  5530.6 2549.10
  5578.2 2551.12  5607.4 2551.47  5636.7 2552.54  5643.2 2553.71  5645.9 2553.71
#Mann=3,-1,0
  4642.7    0.07       0  5015.4    0.07       0  5019.6    0.07       0
Bank Sta=5015.4,5019.6
Exp/Cntr=0.3,0.1

Type RM Length L Ch R = 1,23782,498,498,498
BEGIN DESCRIPTION:
Sweetwater Creek Trib 6 44.0
END DESCRIPTION:
XS GIS Cut Line= 3
      1353154.96      6796238.02      1353556.29      6796084.47
      1353755.01      6795687.98
#Sta/Elev= 30
  4570.3 2544.33  4615.4 2542.77  4640.1 2542.88  4656.0 2541.85  4709.5 2540.64
  4730.9 2539.32  4763.1 2538.13  4773.8 2538.14  4779.7 2537.58  4839.8 2535.14
  4859.1 2534.84  4889.2 2532.98  4943.9 2530.84  4949.3 2529.94  4985.8 2529.09
  4986.1 2528.59  4989.8 2528.59  4990.1 2529.09  5049.7 2530.41  5077.6 2530.11
  5107.9 2530.42  5206.1 2534.95  5228.4 2536.82  5234.0 2536.57  5278.7 2539.18
  5354.0 2541.52  5362.5 2542.39  5384.8 2542.57  5435.1 2544.42  5443.5 2544.35
#Mann=3,-1,0
  4570.3    0.07       0  4985.8    0.07       0  4990.1    0.07       0
Bank Sta=4985.8,4990.1
Exp/Cntr=0.3,0.1

Type RM Length L Ch R = 1,23284,497,497,497
BEGIN DESCRIPTION:
Sweetwater Creek Trib 6 43.0
END DESCRIPTION:
XS GIS Cut Line= 3
      1353755.00      6796837.99      1353899.02      6796335.84
      1353855.00      6795538.05
#Sta/Elev= 30
  4477.6 2545.42  4494.5 2544.04  4560.8 2543.07  4567.1 2542.41  4612.8 2540.95
  4633.6 2541.23  4639.8 2540.37  4706.5 2538.77  4717.7 2538.97  4810.5 2536.24
  4857.9 2533.26  4863.1 2533.64  4924.9 2531.91  4930.6 2531.11  4976.9 2529.08
  5000.0 2527.09  5015.5 2524.41  5015.8 2523.91  5019.9 2523.91  5020.3 2524.41
  5027.9 2525.68  5057.9 2527.12  5178.1 2527.73  5228.2 2530.30  5298.3 2535.35
  5530.2 2542.67  5588.7 2543.63  5618.8 2544.99  5668.9 2545.91  5799.0 2550.85
#Mann=3,-1,0
  4477.6    0.07       0  5015.5    0.07       0  5020.3    0.07       0
Bank Sta=5015.5,5020.3
Exp/Cntr=0.3,0.1

Type RM Length L Ch R = 1,22787,470,470,470
BEGIN DESCRIPTION:
Sweetwater Creek Trib 6 42.0
END DESCRIPTION:
XS GIS Cut Line= 3
      1354004.99      6796638.01      1354364.34      6796237.48
      1354405.01      6796137.97
#Sta/Elev= 30
  4461.9 2537.21  4518.3 2534.81  4603.6 2532.13  4610.3 2532.43  4617.8 2531.65
  4787.5 2525.51  4801.7 2525.83  4809.2 2525.01  4815.9 2525.25  4823.4 2524.63
  4844.3 2524.80  4893.6 2523.46  4929.5 2524.00  4964.6 2523.71  4978.8 2522.90
  4990.6 2520.71  4990.9 2520.21  4995.1 2520.21  4995.5 2520.71  4996.8 2521.49
  5002.4 2521.49  5015.3 2524.33  5021.0 2527.42  5063.3 2533.46  5075.1 2535.58
  5085.9 2536.22  5092.8 2537.76  5098.2 2537.57  5104.8 2539.04  5107.5 2539.04
#Mann=3,-1,0
  4461.9    0.07       0  4990.6    0.07       0  4995.5    0.07       0
Bank Sta=4990.6,4995.5
Exp/Cntr=0.3,0.1

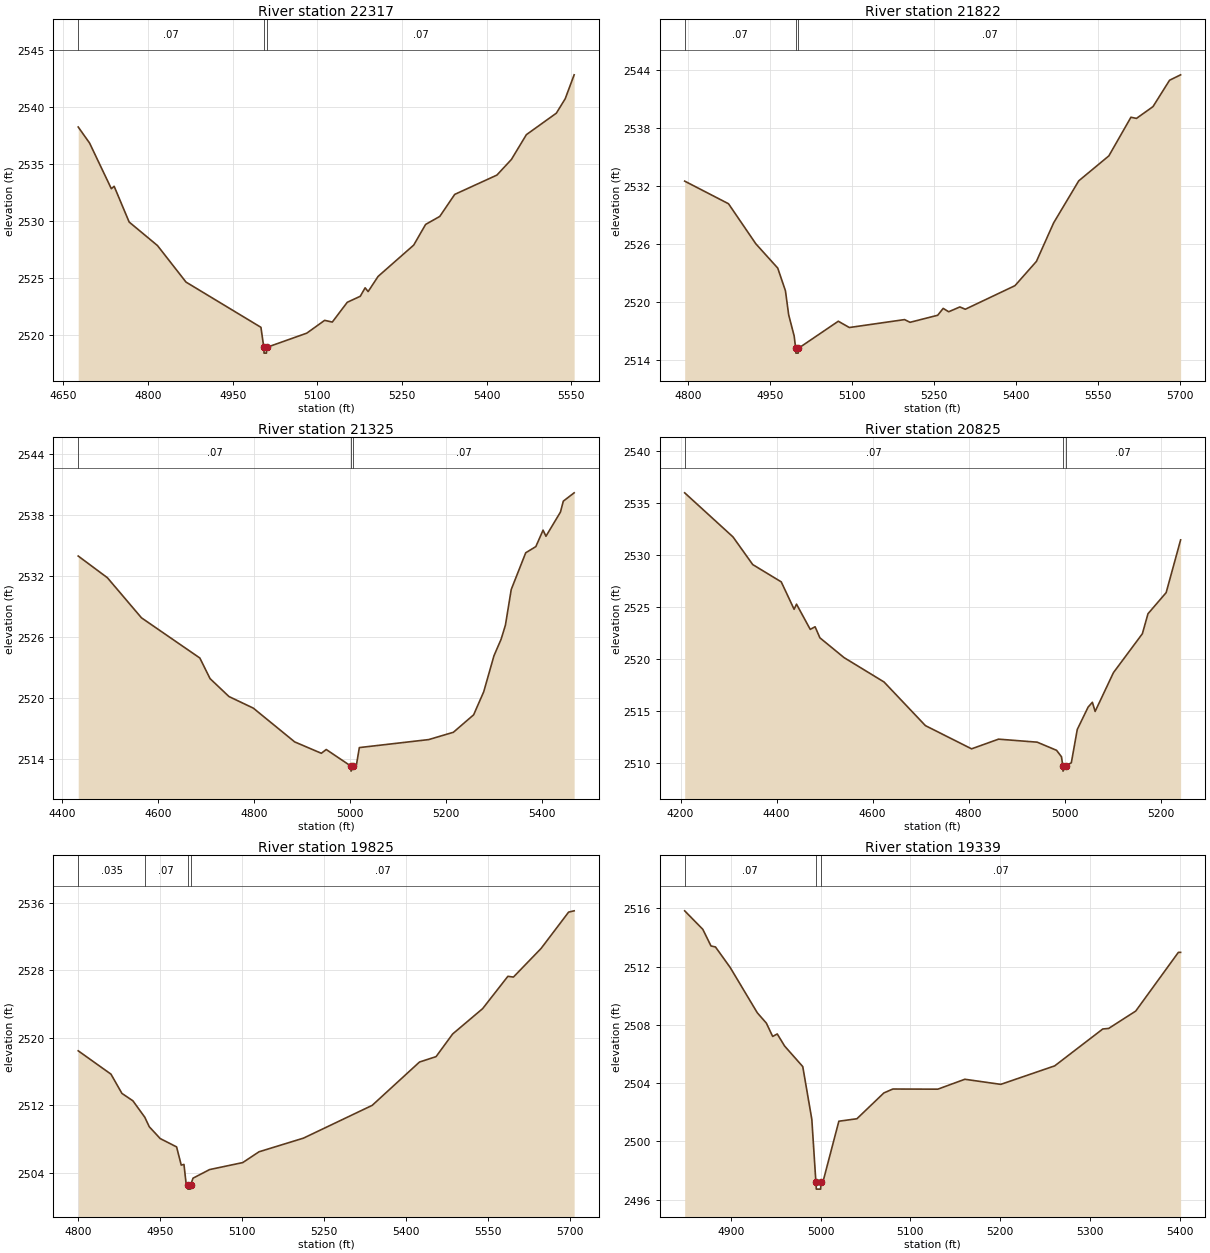
Type RM Length L Ch R = 1,22317,495,495,495
BEGIN DESCRIPTION:
Sweetwater Creek Trib 6 41.0
END DESCRIPTION:
XS GIS Cut Line= 3
      1354605.00      6796888.04      1354631.05      6796565.19
      1354805.02      6796037.95
#Sta/Elev= 30
  4676.1 2538.25  4696.2 2536.85  4734.8 2532.85  4739.8 2533.06  4766.4 2529.93
  4816.6 2527.87  4867.2 2524.67  5000.0 2520.71  5005.1 2518.95  5005.5 2518.45
  5009.7 2518.45  5010.1 2518.95  5081.3 2520.20  5112.9 2521.32  5126.5 2521.17
  5153.0 2522.90  5176.1 2523.43  5184.7 2524.17  5190.0 2523.84  5207.7 2525.17
  5270.8 2527.91  5291.9 2529.72  5317.0 2530.42  5343.5 2532.35  5418.3 2534.04
  5444.0 2535.41  5470.5 2537.58  5523.6 2539.46  5539.3 2540.72  5555.2 2542.82
#Mann=3,-1,0
  4676.1    0.07       0  5005.1    0.07       0  5010.1    0.07       0
Bank Sta=5005.1,5010.1
Exp/Cntr=0.3,0.1

Type RM Length L Ch R = 1,21822,497,497,497
BEGIN DESCRIPTION:
Sweetwater Creek Trib 6 40.0
END DESCRIPTION:
XS GIS Cut Line= 3
      1355055.00      6796888.04      1355049.39      6796682.41
      1354955.00      6795988.00
#Sta/Elev= 30
  4794.3 2532.54  4874.4 2530.20  4924.4 2526.05  4964.4 2523.54  4978.5 2521.19
  4984.4 2518.70  4994.4 2516.52  4997.2 2515.24  4997.6 2514.74  5001.8 2514.74
  5002.2 2515.24  5075.1 2518.04  5095.3 2517.39  5196.2 2518.21  5206.3 2517.93
  5256.8 2518.66  5266.8 2519.37  5276.9 2519.02  5297.3 2519.52  5307.2 2519.28
  5398.0 2521.72  5437.2 2524.23  5468.7 2528.22  5514.6 2532.57  5569.6 2535.15
  5610.0 2539.15  5620.1 2539.03  5650.3 2540.25  5680.6 2542.98  5700.8 2543.54
#Mann=3,-1,0
  4794.3    0.07       0  4997.2    0.07       0  5002.2    0.07       0
Bank Sta=4997.2,5002.2
Exp/Cntr=0.3,0.1

Type RM Length L Ch R = 1,21325,500,500,500
BEGIN DESCRIPTION:
Sweetwater Creek Trib 6 39.0
END DESCRIPTION:
XS GIS Cut Line= 3
      1355505.01      6796938.04      1355410.91      6796379.51
      1355155.02      6795988.02
#Sta/Elev= 30
  4433.6 2533.96  4494.5 2531.82  4565.5 2527.87  4687.2 2523.91  4708.5 2521.88
  4748.0 2520.11  4798.7 2518.97  4885.0 2515.64  4940.5 2514.52  4950.8 2514.89
  5002.1 2513.26  5002.5 2512.76  5007.4 2513.26  5013.7 2513.37  5019.8 2515.08
  5164.6 2515.87  5215.9 2516.59  5258.1 2518.31  5279.2 2520.59  5300.5 2524.13
  5315.4 2525.76  5324.4 2527.15  5336.5 2530.66  5366.7 2534.28  5387.8 2534.89
  5402.9 2536.51  5408.9 2535.91  5439.1 2538.29  5445.1 2539.37  5467.7 2540.19
#Mann=3,-1,0
  4433.6    0.07       0  5002.1    0.07       0  5007.4    0.07       0
Bank Sta=5002.1,5007.4
Exp/Cntr=0.3,0.1

Type RM Length L Ch R = 1,20825,1000,1000,1000
BEGIN DESCRIPTION:
Sweetwater Creek Trib 6 38.0
END DESCRIPTION:
XS GIS Cut Line= 3
      1355705.00      6796988.04      1355791.21      6796201.35
      1355905.00      6795988.00
#Sta/Elev= 30
  4208.6 2535.96  4309.2 2531.73  4350.4 2529.07  4409.8 2527.41  4436.6 2524.78
  4441.6 2525.27  4470.2 2522.85  4480.3 2523.10  4490.3 2522.04  4540.6 2520.14
  4623.9 2517.80  4710.1 2513.61  4806.3 2511.38  4862.5 2512.31  4943.0 2512.02
  4983.3 2511.24  4993.6 2510.62  4996.4 2509.74  4996.8 2509.24  5002.0 2509.74
  5014.1 2510.04  5026.5 2513.24  5049.1 2515.39  5058.0 2515.85  5063.7 2514.97
  5101.9 2518.70  5162.1 2522.43  5173.8 2524.35  5211.7 2526.38  5241.8 2531.44
#Mann=3,-1,0
  4208.6    0.07       0  4996.4    0.07       0  5002.0    0.07       0
Bank Sta=4996.4,5002
Exp/Cntr=0.3,0.1

Type RM Length L Ch R = 1,19825,486,486,486
BEGIN DESCRIPTION:
Sweetwater Creek Trib 6 37.0
END DESCRIPTION:
XS GIS Cut Line= 3
      1356405.00      6796838.02      1356410.20      6796638.48
      1356305.01      6795938.04
#Sta/Elev= 30
  4800.4 2518.46  4860.4 2515.69  4880.4 2513.41  4900.5 2512.53  4922.3 2510.58
  4930.5 2509.45  4950.5 2508.05  4980.5 2507.06  4989.0 2504.90  4994.0 2504.98
  4997.7 2502.84  5000.6 2502.55  5001.1 2502.05  5005.8 2502.05  5006.2 2502.55
  5010.6 2503.35  5040.9 2504.37  5101.6 2505.20  5131.4 2506.48  5212.8 2508.10
  5338.6 2511.99  5425.2 2517.13  5455.5 2517.77  5485.9 2520.46  5540.7 2523.46
  5587.0 2527.30  5597.1 2527.21  5647.7 2530.60  5698.2 2534.92  5708.3 2535.07
#Mann=4,-1,0
  4800.4   0.035       0  4922.3    0.07       0  5000.6    0.07       0
  5006.2    0.07       0
Bank Sta=5000.6,5006.2
Exp/Cntr=0.3,0.1

Type RM Length L Ch R = 1,19339,470,470,470
BEGIN DESCRIPTION:
Sweetwater Creek Trib 6 36.0
END DESCRIPTION:
XS GIS Cut Line= 3
      1356805.00      6796787.99      1356827.71      6796638.40
      1356805.00      6796238.05
#Sta/Elev= 30
  4848.7 2515.83  4868.9 2514.56  4878.0 2513.42  4883.0 2513.35  4899.3 2511.95
  4929.6 2508.83  4939.7 2508.12  4946.7 2507.21  4951.8 2507.38  4960.0 2506.55
  4980.2 2505.14  4990.3 2501.52  4994.8 2497.23  4995.3 2496.73  5000.1 2496.73
  5000.5 2497.23  5002.7 2497.23  5020.4 2501.39  5040.5 2501.56  5070.5 2503.33
  5080.5 2503.60  5130.6 2503.59  5160.7 2504.27  5200.7 2503.92  5260.8 2505.19
  5314.3 2507.72  5320.9 2507.76  5351.0 2508.95  5398.5 2512.98  5401.0 2512.98
#Mann=3,-1,0
  4848.7    0.07       0  4994.8    0.07       0  5000.5    0.07       0
Bank Sta=4994.8,5000.5
Exp/Cntr=0.3,0.1

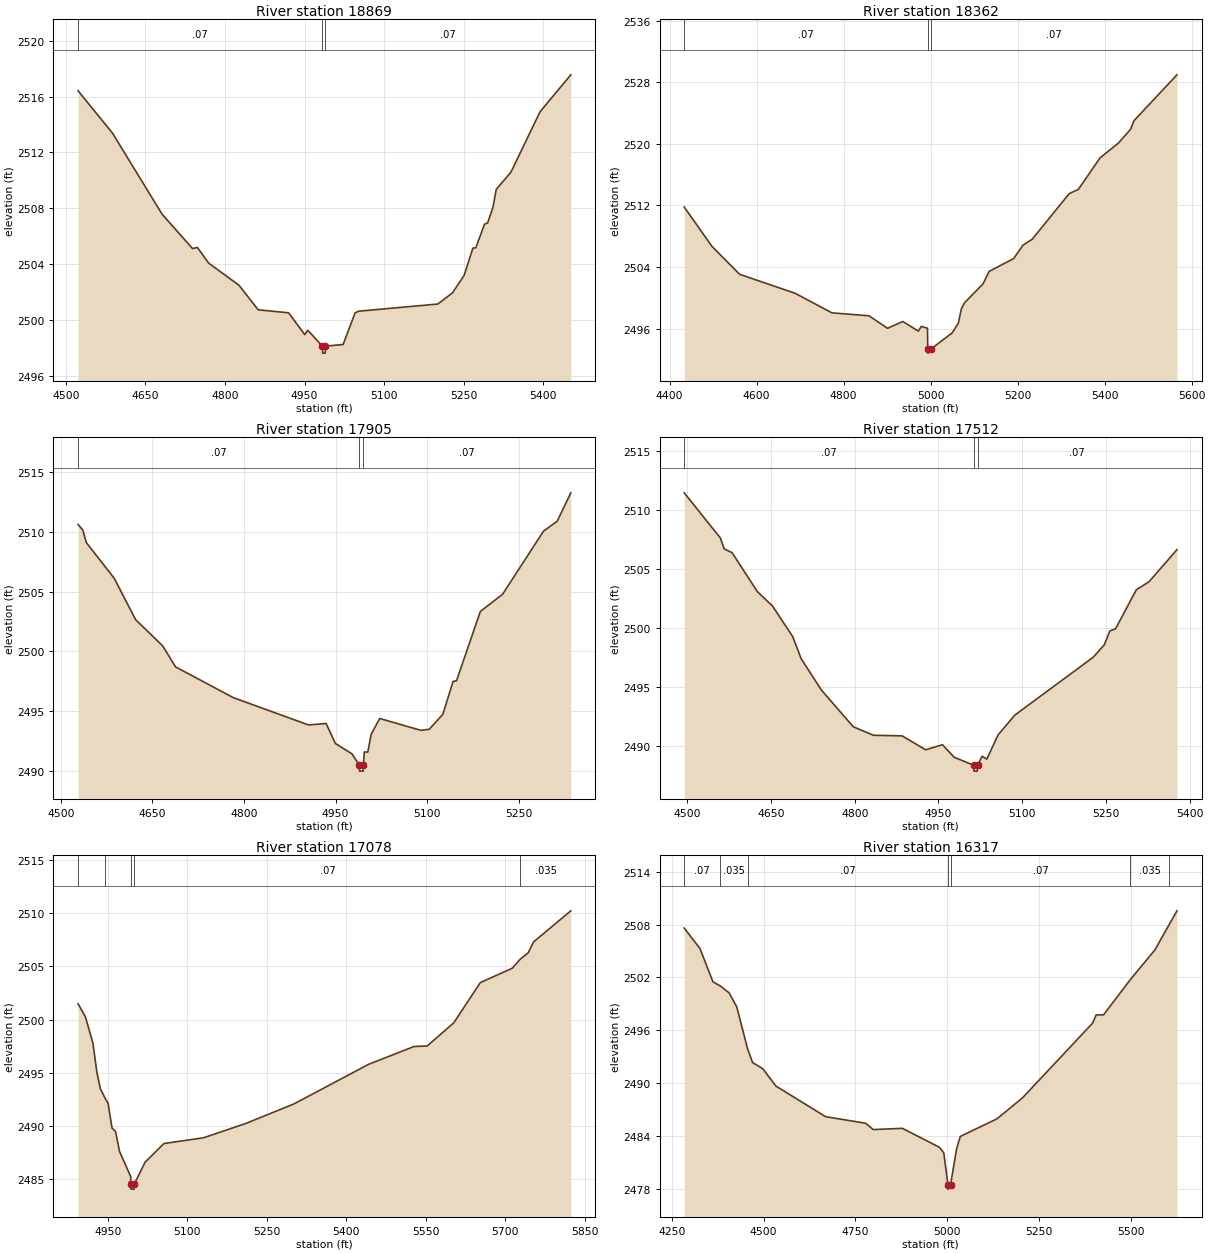
Type RM Length L Ch R = 1,18869,507,507,507
BEGIN DESCRIPTION:
Sweetwater Creek Trib 6 35.0
END DESCRIPTION:
XS GIS Cut Line= 3
      1357005.00      6796937.99      1357265.05      6796538.11
      1357055.00      6796137.99
#Sta/Elev= 30
  4523.0 2516.43  4587.9 2513.39  4681.5 2507.57  4738.8 2505.11  4748.0 2505.19
  4769.1 2504.07  4826.4 2502.48  4862.6 2500.72  4920.0 2500.50  4950.3 2498.94
  4956.2 2499.25  4983.6 2498.11  4984.1 2497.61  4988.9 2497.61  4989.3 2498.11
  5022.7 2498.23  5045.3 2500.50  5052.4 2500.62  5201.1 2501.13  5228.8 2501.93
  5250.9 2503.19  5267.3 2505.14  5272.9 2505.17  5289.3 2506.86  5295.0 2506.94
  5305.1 2508.07  5311.4 2509.36  5339.1 2510.59  5393.9 2514.92  5451.9 2517.57
#Mann=3,-1,0
  4523.0    0.07       0  4983.6    0.07       0  4989.3    0.07       0
Bank Sta=4983.6,4989.3
Exp/Cntr=0.3,0.1

Type RM Length L Ch R = 1,18362,457,457,457
BEGIN DESCRIPTION:
Sweetwater Creek Trib 6 34.0
END DESCRIPTION:
XS GIS Cut Line= 3
      1357205.02      6796987.98      1357624.87      6796607.79
      1358004.98      6796188.02
#Sta/Elev= 30
  4433.6 2511.78  4497.4 2506.68  4561.0 2503.05  4688.7 2500.58  4773.2 2498.04
  4858.3 2497.66  4900.9 2496.04  4936.1 2496.92  4971.9 2495.67  4978.6 2496.28
  4992.8 2496.05  4993.5 2493.31  4994.0 2492.81  5000.0 2493.31  5049.6 2495.44
  5063.8 2496.71  5070.6 2498.56  5078.0 2499.36  5120.6 2501.81  5134.6 2503.43
  5190.9 2505.09  5212.5 2506.84  5233.5 2507.60  5318.6 2513.53  5339.6 2514.08
  5389.6 2518.18  5431.5 2520.08  5459.9 2521.90  5467.3 2522.99  5566.3 2528.96
#Mann=3,-1,0
  4433.6    0.07       0  4993.5    0.07       0  5000.0    0.07       0
Bank Sta=4993.5,5000
Exp/Cntr=0.3,0.1

Type RM Length L Ch R = 1,17905,393,393,393
BEGIN DESCRIPTION:
Sweetwater Creek Trib 6 33.0
END DESCRIPTION:
XS GIS Cut Line= 3
      1357654.99      6797238.01      1357905.03      6796837.92
      1358054.99      6796538.02
#Sta/Elev= 30
  4528.2 2510.63  4535.9 2510.17  4541.8 2509.11  4587.2 2506.14  4622.6 2502.65
  4666.8 2500.46  4688.0 2498.70  4782.3 2496.13  4905.6 2493.84  4934.5 2493.96
  4949.8 2492.28  4976.9 2491.42  4988.9 2490.47  4989.4 2489.97  4995.2 2489.97
  4995.7 2490.47  4997.0 2491.57  5002.8 2491.57  5008.3 2493.05  5022.3 2494.38
  5089.4 2493.39  5103.3 2493.47  5125.7 2494.73  5142.5 2497.48  5148.1 2497.54
  5187.2 2503.35  5223.5 2504.78  5290.6 2510.07  5313.0 2510.90  5335.3 2513.28
#Mann=3,-1,0
  4528.2    0.07       0  4988.9    0.07       0  4995.7    0.07       0
Bank Sta=4988.9,4995.7
Exp/Cntr=0.3,0.1

Type RM Length L Ch R = 1,17512,434,434,434
BEGIN DESCRIPTION:
Sweetwater Creek Trib 6 32.0
END DESCRIPTION:
XS GIS Cut Line= 3
      1357955.02      6797437.98      1358231.75      6797014.59
      1358205.00      6796638.04
#Sta/Elev= 30
  4494.2 2511.45  4559.0 2507.62  4565.8 2506.70  4580.1 2506.37  4625.4 2503.07
  4652.5 2501.85  4688.7 2499.26  4703.8 2497.39  4740.0 2494.73  4797.3 2491.61
  4833.5 2490.89  4884.8 2490.84  4927.0 2489.66  4957.2 2490.09  4978.3 2489.02
  5013.2 2488.35  5013.7 2487.85  5019.5 2487.85  5020.0 2488.35  5028.2 2489.11
  5036.7 2488.87  5056.7 2490.91  5086.8 2492.60  5227.2 2497.50  5247.2 2498.56
  5257.2 2499.74  5267.3 2499.91  5304.7 2503.23  5327.4 2503.91  5377.5 2506.63
#Mann=3,-1,0
  4494.2    0.07       0  5013.2    0.07       0  5020.0    0.07       0
Bank Sta=5013.2,5020
Exp/Cntr=0.3,0.1

Type RM Length L Ch R = 1,17078,761,761,761
BEGIN DESCRIPTION:
Sweetwater Creek Trib 6 31.0
END DESCRIPTION:
XS GIS Cut Line= 3
      1358404.99      6797438.01      1358474.81      6797358.51
      1358405.00      6796537.97
#Sta/Elev= 30
  4894.2 2501.49  4908.0 2500.27  4922.2 2497.80  4929.8 2495.01  4936.4 2493.49
  4944.8 2492.64  4950.7 2492.15  4958.3 2489.79  4964.9 2489.48  4972.5 2487.59
  4993.4 2485.24  4993.6 2484.55  4994.1 2484.05  5000.0 2484.05  5000.5 2484.55
  5020.6 2486.58  5056.2 2488.34  5131.0 2488.88  5211.3 2490.24  5301.6 2492.07
  5442.1 2495.79  5528.0 2497.47  5552.5 2497.51  5602.7 2499.69  5652.9 2503.48
  5713.1 2504.83  5728.3 2505.69  5743.2 2506.28  5753.2 2507.30  5823.5 2510.23
#Mann=5,-1,0
  4894.2   0.035       0  4944.8    0.07       0  4993.6    0.07       0
  5000.5    0.07       0  5728.3   0.035       0
Bank Sta=4993.6,5000.5
Exp/Cntr=0.3,0.1

Type RM Length L Ch R = 1,16317,703,703,703
BEGIN DESCRIPTION:
Sweetwater Creek Trib 6 30.0
END DESCRIPTION:
XS GIS Cut Line= 3
      1358554.97      6797638.02      1359132.30      6797213.84
      1359155.00      6796587.96
#Sta/Elev= 30
  4283.6 2507.60  4326.5 2505.28  4362.0 2501.48  4380.5 2501.06  4405.9 2500.24
  4426.8 2498.64  4456.1 2493.91  4469.8 2492.32  4497.8 2491.61  4533.3 2489.65
  4669.1 2486.16  4777.8 2485.42  4798.7 2484.70  4878.1 2484.84  4978.4 2482.70
  4990.9 2482.06  5002.3 2478.43  5002.8 2477.93  5009.3 2478.43  5025.9 2482.52
  5035.9 2483.92  5135.9 2485.92  5206.0 2488.33  5396.1 2496.78  5406.1 2497.73
  5426.1 2497.73  5499.6 2501.76  5566.2 2505.12  5605.4 2508.02  5626.3 2509.56
#Mann=7,-1,0
  4283.6    0.07       0  4380.5   0.035       0  4456.1    0.07       0
  5002.3    0.07       0  5009.3    0.07       0  5499.6   0.035       0
  5605.4    0.07       0
Bank Sta=5002.3,5009.3
Exp/Cntr=0.3,0.1

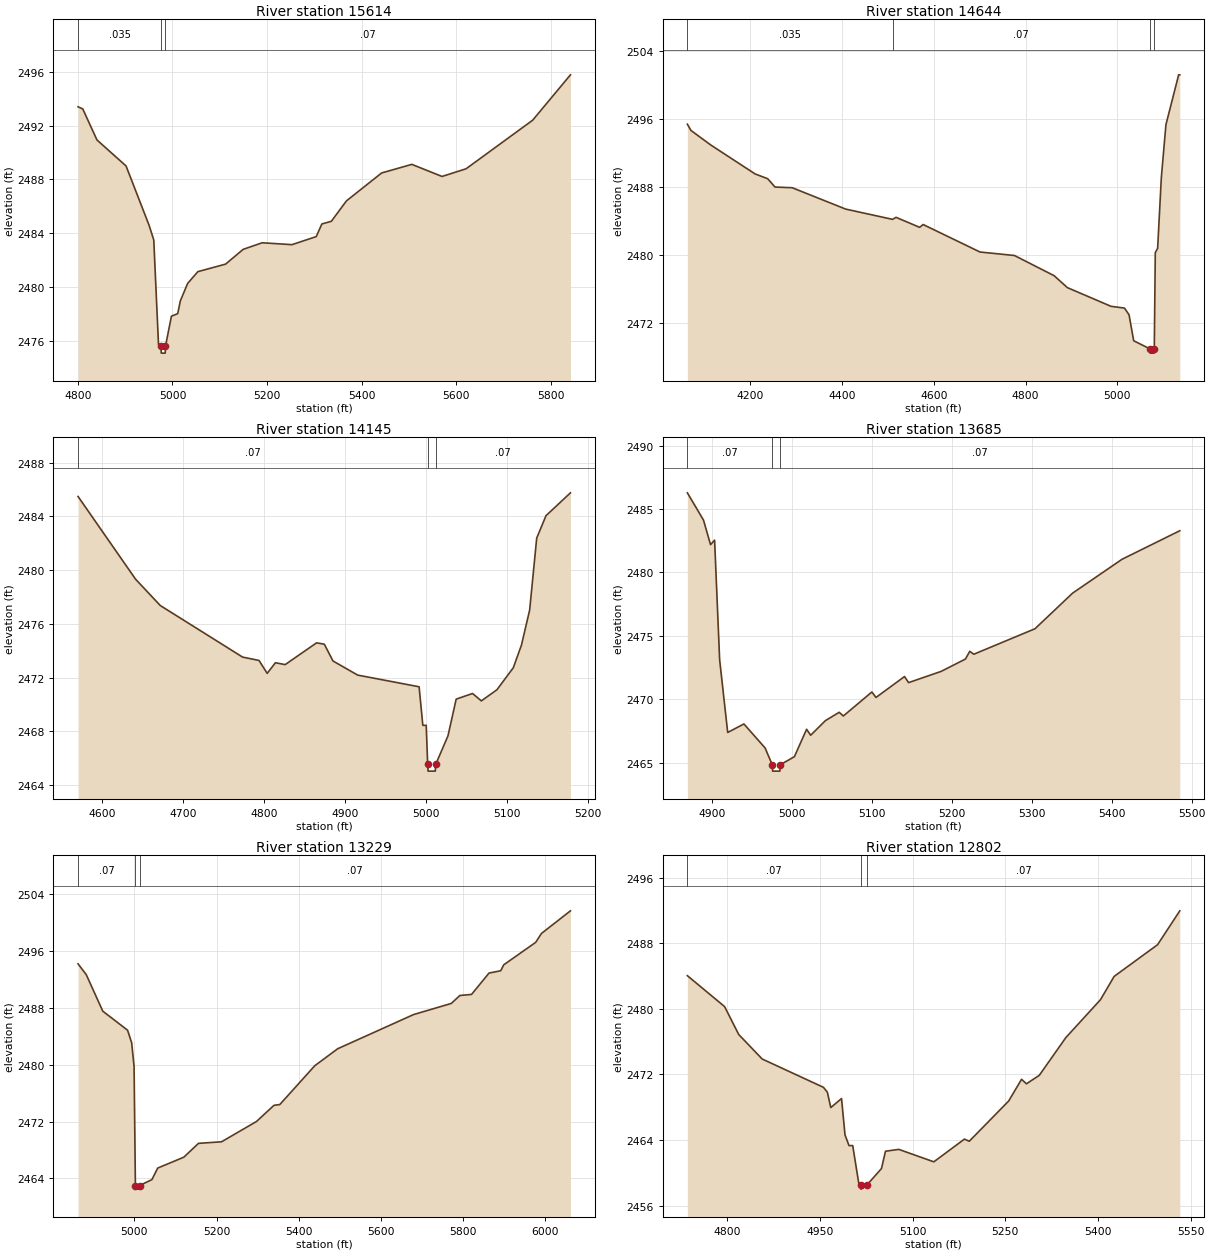
Type RM Length L Ch R = 1,15614,970,970,970
BEGIN DESCRIPTION:
Sweetwater Creek Trib 6 29.0
END DESCRIPTION:
XS GIS Cut Line= 3
      1359455.00      6797837.99      1359465.19      6797638.55
      1359204.99      6796837.97
#Sta/Elev= 30
  4800.3 2493.41  4810.3 2493.25  4840.3 2490.94  4901.9 2489.00  4950.5 2484.59
  4960.5 2483.49  4970.5 2475.70  4975.8 2475.56  4976.3 2475.06  4984.7 2475.06
  4985.2 2475.56  4997.8 2477.81  5011.1 2478.00  5016.6 2478.94  5032.1 2480.25
  5053.8 2481.13  5112.4 2481.69  5149.6 2482.79  5189.8 2483.28  5252.9 2483.14
  5304.1 2483.74  5316.0 2484.68  5336.1 2484.88  5368.0 2486.40  5442.4 2488.48
  5506.3 2489.12  5570.2 2488.22  5621.0 2488.79  5761.9 2492.41  5841.8 2495.79
#Mann=3,-1,0
  4800.3   0.035       0  4975.8    0.07       0  4985.2    0.07       0
Bank Sta=4975.8,4985.2
Exp/Cntr=0.3,0.1

Type RM Length L Ch R = 1,14644,499,499,499
BEGIN DESCRIPTION:
Sweetwater Creek Trib 6 28.0
END DESCRIPTION:
XS GIS Cut Line= 3
      1359755.00      6797888.00      1360218.24      6797073.52
      1360205.00      6796937.97
#Sta/Elev= 30
  4063.0 2495.42  4070.9 2494.68  4114.2 2492.96  4210.8 2489.55  4238.1 2488.99
  4254.0 2488.01  4291.5 2487.93  4408.1 2485.41  4510.2 2484.20  4517.8 2484.44
  4569.2 2483.26  4576.9 2483.59  4700.8 2480.35  4775.8 2479.94  4862.3 2477.56
  4891.3 2476.15  4986.2 2473.95  5015.6 2473.74  5025.6 2472.95  5035.7 2469.89
  5071.2 2468.93  5071.7 2468.43  5080.1 2468.43  5080.6 2468.93  5082.8 2480.28
  5087.9 2480.78  5096.0 2489.16  5106.0 2495.36  5133.7 2501.24  5136.2 2501.24
#Mann=4,-1,0
  4063.0   0.035       0  4510.2    0.07       0  5071.2    0.07       0
  5080.6    0.07       0
Bank Sta=5071.2,5080.6
Exp/Cntr=0.3,0.1

Type RM Length L Ch R = 1,14145,460,460,460
BEGIN DESCRIPTION:
Sweetwater Creek Trib 6 27.0
END DESCRIPTION:
XS GIS Cut Line= 3
      1360405.00      6797838.01      1360481.62      6797414.69
      1360505.00      6797238.03
#Sta/Elev= 30
  4569.8 2485.48  4640.9 2479.32  4671.4 2477.36  4773.1 2473.52  4793.4 2473.27
  4803.5 2472.31  4813.7 2473.10  4825.7 2472.96  4864.5 2474.58  4874.1 2474.48
  4884.8 2473.23  4915.3 2472.18  4991.2 2471.31  4995.8 2468.44  5000.0 2468.44
  5001.8 2465.53  5002.3 2465.03  5011.2 2465.03  5011.7 2465.53  5026.9 2467.66
  5037.0 2470.39  5057.2 2470.81  5068.1 2470.26  5087.4 2471.09  5107.6 2472.73
  5117.7 2474.42  5127.8 2477.03  5136.5 2482.38  5148.0 2484.05  5178.2 2485.75
#Mann=3,-1,0
  4569.8    0.07       0  5001.8    0.07       0  5011.7    0.07       0
Bank Sta=5001.8,5011.7
Exp/Cntr=0.3,0.1

Type RM Length L Ch R = 1,13685,456,456,456
BEGIN DESCRIPTION:
Sweetwater Creek Trib 6 26.0
END DESCRIPTION:
XS GIS Cut Line= 3
      1360755.01      6797887.96      1360775.00      6797758.09
      1360654.99      6797287.97
#Sta/Elev= 30
  4868.6 2486.27  4888.8 2484.12  4897.6 2482.18  4902.7 2482.54  4909.0 2473.11
  4919.1 2467.37  4939.4 2468.04  4965.9 2466.15  4974.9 2464.82  4975.4 2464.32
  4984.4 2464.32  4984.9 2464.82  5002.6 2465.46  5017.9 2467.62  5023.0 2467.15
  5041.4 2468.30  5058.7 2468.96  5063.9 2468.67  5099.6 2470.56  5104.8 2470.13
  5140.5 2471.78  5145.6 2471.30  5186.5 2472.19  5216.8 2473.16  5222.2 2473.77
  5227.3 2473.54  5303.9 2475.55  5351.0 2478.36  5412.9 2481.03  5485.2 2483.28
#Mann=3,-1,0
  4868.6    0.07       0  4974.9    0.07       0  4984.9    0.07       0
Bank Sta=4974.9,4984.9
Exp/Cntr=0.3,0.1

Type RM Length L Ch R = 1,13229,427,427,427
BEGIN DESCRIPTION:
Sweetwater Creek Trib 6 25.0
END DESCRIPTION:
XS GIS Cut Line= 3
      1361105.00      6797738.03      1361091.76      6797601.37
      1360305.02      6796888.02
#Sta/Elev= 30
  4862.7 2494.22  4882.8 2492.69  4923.0 2487.55  4983.3 2484.87  4993.3 2483.11
  4999.2 2479.74  5002.4 2462.97  5002.9 2462.47  5011.9 2462.47  5012.4 2462.97
  5042.6 2463.81  5056.8 2465.44  5120.3 2466.97  5156.1 2468.92  5212.2 2469.14
  5297.3 2472.00  5339.9 2474.28  5354.1 2474.39  5439.3 2479.86  5495.3 2482.26
  5679.9 2487.07  5771.8 2488.64  5792.7 2489.76  5821.1 2489.91  5863.7 2492.92
  5892.1 2493.24  5899.5 2494.08  5977.2 2497.24  5991.4 2498.50  6062.0 2501.69
#Mann=3,-1,0
  4862.7    0.07       0  5002.4    0.07       0  5012.4    0.07       0
Bank Sta=5002.4,5012.4
Exp/Cntr=0.3,0.1

Type RM Length L Ch R = 1,12802,496,496,496
BEGIN DESCRIPTION:
Sweetwater Creek Trib 6 24.0
END DESCRIPTION:
XS GIS Cut Line= 3
      1361405.00      6797488.00      1361294.50      6797247.79
      1360954.97      6796837.97
#Sta/Elev= 30
  4735.6 2484.04  4795.8 2480.27  4818.7 2476.86  4856.7 2473.87  4955.7 2470.42
  4962.1 2469.82  4967.6 2467.95  4985.0 2469.05  4990.6 2464.61  4997.1 2463.31
  5003.1 2463.31  5013.1 2458.61  5015.9 2458.50  5016.4 2458.00  5026.0 2458.50
  5049.6 2460.51  5056.1 2462.62  5077.6 2462.85  5134.3 2461.33  5183.8 2464.10
  5191.6 2463.84  5255.4 2468.75  5276.2 2471.40  5284.1 2470.85  5304.9 2471.88
  5347.9 2476.49  5403.9 2481.11  5426.0 2483.95  5496.3 2487.82  5532.2 2491.95
#Mann=3,-1,0
  4735.6    0.07       0  5015.9    0.07       0  5026.0    0.07       0
Bank Sta=5015.9,5026
Exp/Cntr=0.3,0.1

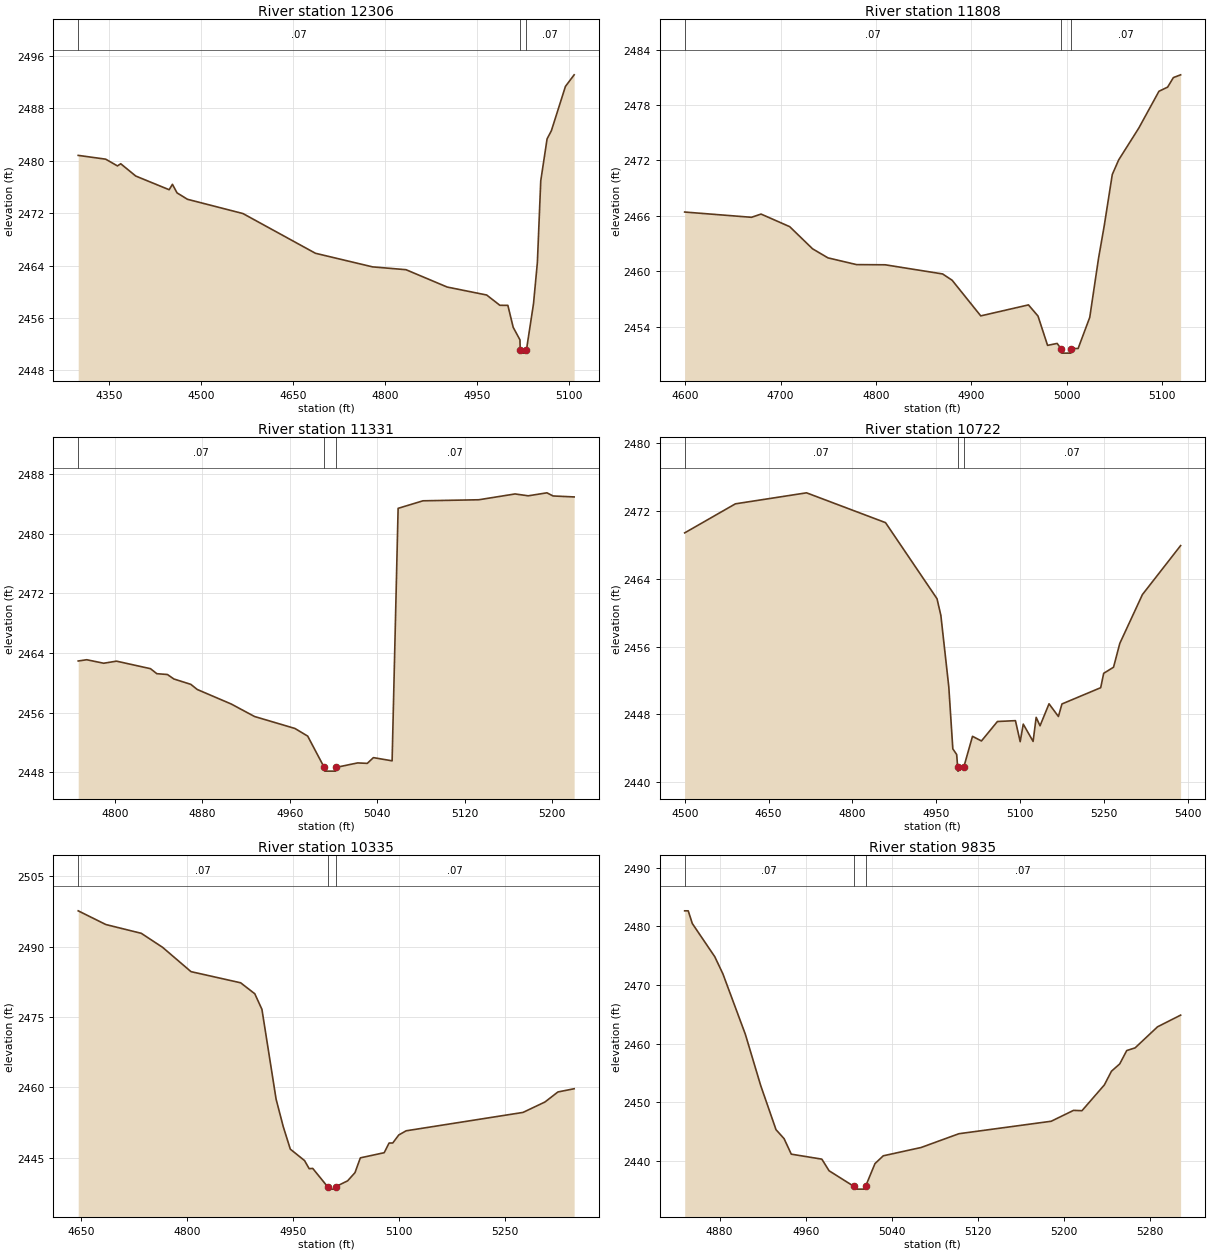
Type RM Length L Ch R = 1,12306,498,498,498
BEGIN DESCRIPTION:
Sweetwater Creek Trib 6 23.0
END DESCRIPTION:
XS GIS Cut Line= 3
      1361655.01      6797438.03      1361400.63      6796785.89
      1361355.00      6796688.00
#Sta/Elev= 30
  4300.0 2480.83  4344.8 2480.25  4363.9 2479.22  4369.3 2479.55  4393.8 2477.67
  4448.2 2475.58  4453.5 2476.41  4461.0 2475.10  4478.0 2474.12  4568.4 2471.94
  4686.5 2465.87  4779.6 2463.79  4834.0 2463.36  4901.1 2460.71  4965.5 2459.49
  4987.0 2457.92  5000.0 2457.91  5008.7 2454.55  5019.7 2452.64  5020.1 2451.11
  5020.6 2450.61  5029.8 2450.61  5030.3 2451.11  5041.8 2458.17  5048.1 2464.48
  5053.6 2476.95  5063.9 2483.35  5070.9 2484.60  5093.8 2491.37  5108.0 2493.14
#Mann=3,-1,0
  4300.0    0.07       0  5020.1    0.07       0  5030.3    0.07       0
Bank Sta=5020.1,5030.3
Exp/Cntr=0.3,0.1

Type RM Length L Ch R = 1,11808,477,477,477
BEGIN DESCRIPTION:
Sweetwater Creek Trib 6 22.0
END DESCRIPTION:
XS GIS Cut Line= 3
      1361805.00      6796937.97      1361789.94      6796537.85
      1361855.01      6796437.98
#Sta/Elev= 30
  4599.6 2466.42  4669.6 2465.85  4679.6 2466.20  4709.6 2464.84  4733.6 2462.44
  4749.7 2461.46  4779.7 2460.73  4809.7 2460.71  4869.8 2459.72  4879.8 2459.04
  4909.8 2455.18  4959.8 2456.37  4969.8 2455.16  4979.8 2451.99  4989.8 2452.20
  4993.8 2451.65  4994.3 2451.15  5004.1 2451.15  5004.6 2451.65  5011.8 2451.65
  5024.0 2455.02  5033.2 2461.41  5039.2 2464.95  5047.6 2470.48  5054.3 2472.06
  5075.4 2475.51  5096.5 2479.49  5105.6 2479.94  5111.6 2480.97  5119.2 2481.27
#Mann=3,-1,0
  4599.6    0.07       0  4993.8    0.07       0  5004.6    0.07       0
Bank Sta=4993.8,5004.6
Exp/Cntr=0.3,0.1

Type RM Length L Ch R = 1,11331,609,609,609
BEGIN DESCRIPTION:
Sweetwater Creek Trib 6 21.0
END DESCRIPTION:
XS GIS Cut Line= 3
      1361955.00      6796838.00      1362155.24      6796717.89
      1362250.12      6796519.29
#Sta/Elev= 30
  4766.5 2462.94  4774.3 2463.11  4789.8 2462.64  4801.5 2462.92  4832.6 2461.91
  4838.4 2461.24  4848.1 2461.13  4854.0 2460.53  4869.5 2459.81  4875.4 2459.12
  4906.4 2457.18  4927.8 2455.50  4964.7 2453.90  4976.4 2452.87  4991.5 2448.68
  4992.0 2448.18  5001.9 2448.18  5002.4 2448.68  5022.0 2449.28  5030.9 2449.22
  5036.5 2449.99  5053.6 2449.56  5059.1 2483.40  5081.8 2484.41  5132.9 2484.55
  5166.1 2485.33  5178.1 2485.08  5195.2 2485.48  5200.8 2485.06  5220.1 2484.93
#Mann=3,-1,0
  4766.5    0.07       0  4991.5    0.07       0  5002.4    0.07       0
Bank Sta=4991.5,5002.4
Exp/Cntr=0.3,0.1

Type RM Length L Ch R = 1,10722,387,387,387
BEGIN DESCRIPTION:
Sweetwater Creek Trib 6 20.0
END DESCRIPTION:
XS GIS Cut Line= 3
      1361876.35      6797617.48      1362237.45      6797271.35
      1362397.40      6796918.95
#Sta/Elev= 30
  4499.8 2469.43  4590.5 2472.86  4717.8 2474.16  4859.1 2470.64  4951.2 2461.66
  4958.1 2459.69  4972.3 2451.24  4979.5 2443.93  4986.4 2443.26  4988.1 2441.80
  4988.6 2441.30  4999.2 2441.80  5014.7 2445.41  5030.7 2444.86  5059.3 2447.16
  5091.5 2447.26  5100.0 2444.78  5105.5 2446.85  5123.1 2444.81  5128.6 2447.65
  5135.5 2446.65  5151.6 2449.25  5168.4 2447.75  5174.7 2449.23  5244.0 2451.15
  5249.4 2452.85  5267.0 2453.57  5278.2 2456.38  5318.7 2462.15  5387.0 2467.93
#Mann=3,-1,0
  4499.8    0.07       0  4988.1    0.07       0  4999.2    0.07       0
Bank Sta=4988.1,4999.2
Exp/Cntr=0.3,0.1

Type RM Length L Ch R = 1,10335,500,500,500
BEGIN DESCRIPTION:
Sweetwater Creek Trib 6 19.0
END DESCRIPTION:
XS GIS Cut Line= 3
      1362514.72      6797776.90      1362541.96      6797424.46
      1362455.00      6797088.01
#Sta/Elev= 30
  4646.5 2497.67  4685.5 2494.75  4735.7 2492.87  4765.8 2489.88  4805.9 2484.70
  4876.1 2482.32  4896.1 2479.98  4906.2 2476.65  4926.2 2457.50  4936.3 2451.65
  4946.3 2446.84  4966.4 2444.40  4973.0 2442.67  4978.0 2442.73  4999.1 2438.81
  4999.6 2438.31  5009.7 2438.31  5010.2 2438.81  5027.3 2440.08  5037.7 2441.82
  5045.3 2444.98  5079.0 2446.08  5085.9 2448.14  5091.1 2448.15  5099.6 2449.86
  5110.0 2450.75  5275.2 2454.67  5306.2 2456.89  5324.6 2459.04  5347.5 2459.72
#Mann=3,-1,0
  4646.5    0.07       0  4999.1    0.07       0  5010.2    0.07       0
Bank Sta=4999.1,5010.2
Exp/Cntr=0.3,0.1

Type RM Length L Ch R = 1,9835,497,497,497
BEGIN DESCRIPTION:
Sweetwater Creek Trib 6 18.0
END DESCRIPTION:
XS GIS Cut Line= 3
      1362954.99      6797237.99      1362853.82      6797123.87
      1362654.99      6796887.99
#Sta/Elev= 30
  4847.5 2482.66  4850.8 2482.66  4854.6 2480.49  4875.5 2474.82  4883.0 2471.91
  4903.9 2461.58  4918.1 2452.87  4932.4 2445.29  4939.9 2443.76  4946.6 2441.11
  4975.0 2440.26  4981.7 2438.28  5004.5 2435.64  5005.0 2435.14  5015.2 2435.14
  5015.7 2435.64  5024.4 2439.50  5032.1 2440.83  5067.3 2442.25  5102.4 2444.60
  5188.2 2446.73  5209.0 2448.59  5216.8 2448.53  5237.6 2452.93  5244.2 2455.27
  5251.9 2456.52  5258.4 2458.80  5266.2 2459.26  5287.0 2462.85  5308.5 2464.85
#Mann=3,-1,0
  4847.5    0.07       0  5004.5    0.07       0  5015.7    0.07       0
Bank Sta=5004.5,5015.7
Exp/Cntr=0.3,0.1