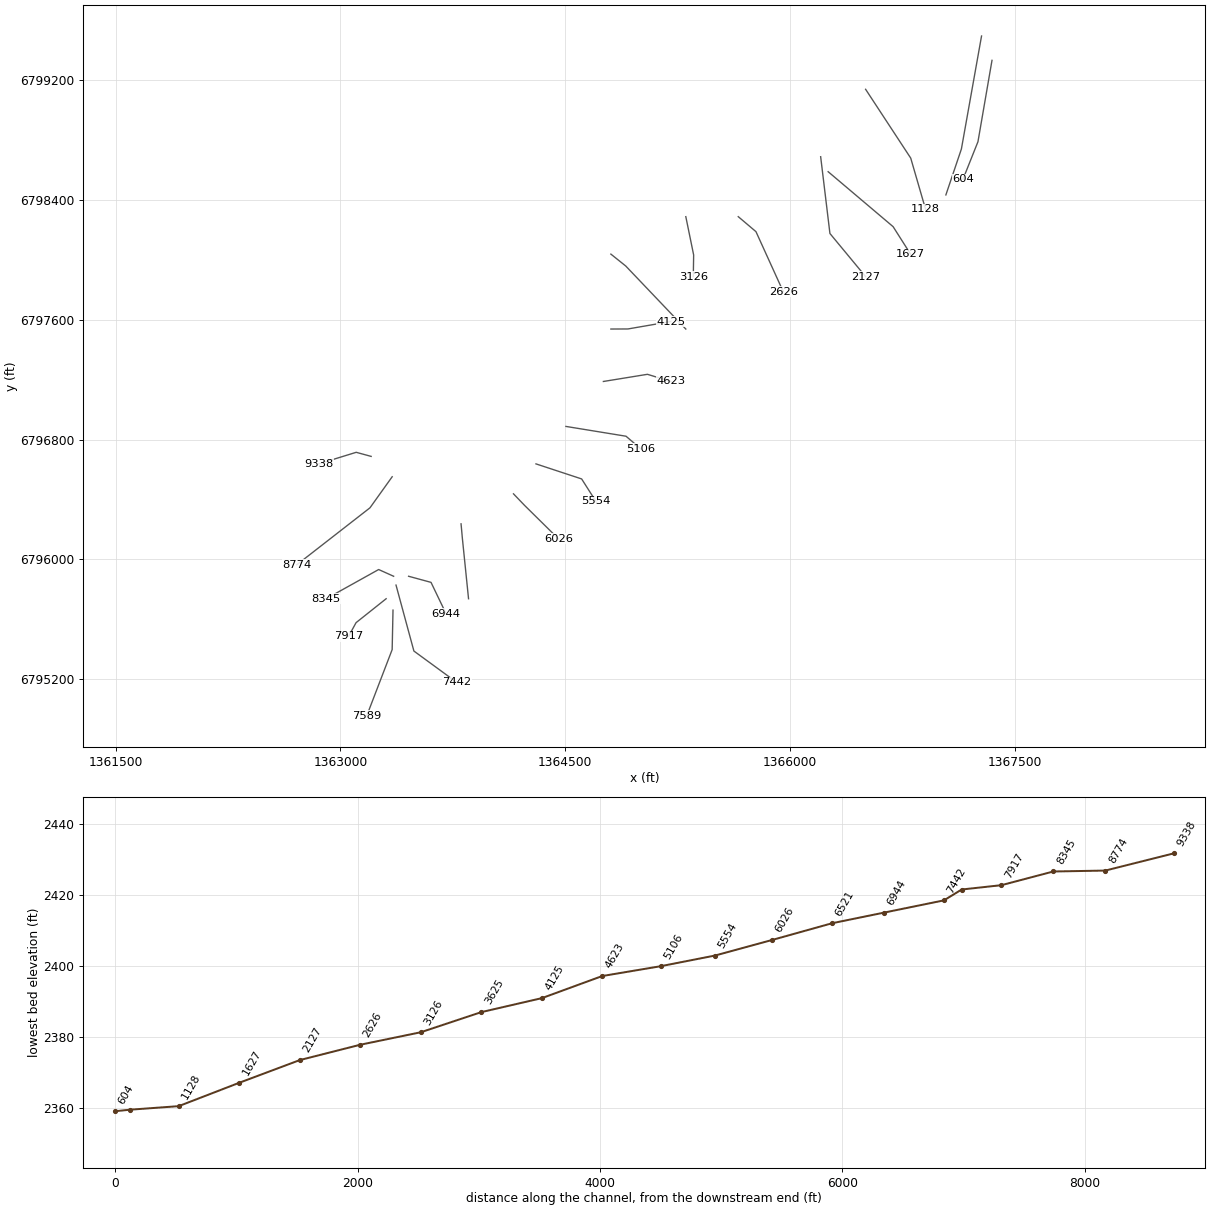
HEC-RAS study Sweetwater Creek Trib 6.prj: Sweetwater Creek Trib 6 Base Level Engineering

--- Sweetwater Creek Trib 6.g01 (geometry) --- (continued)

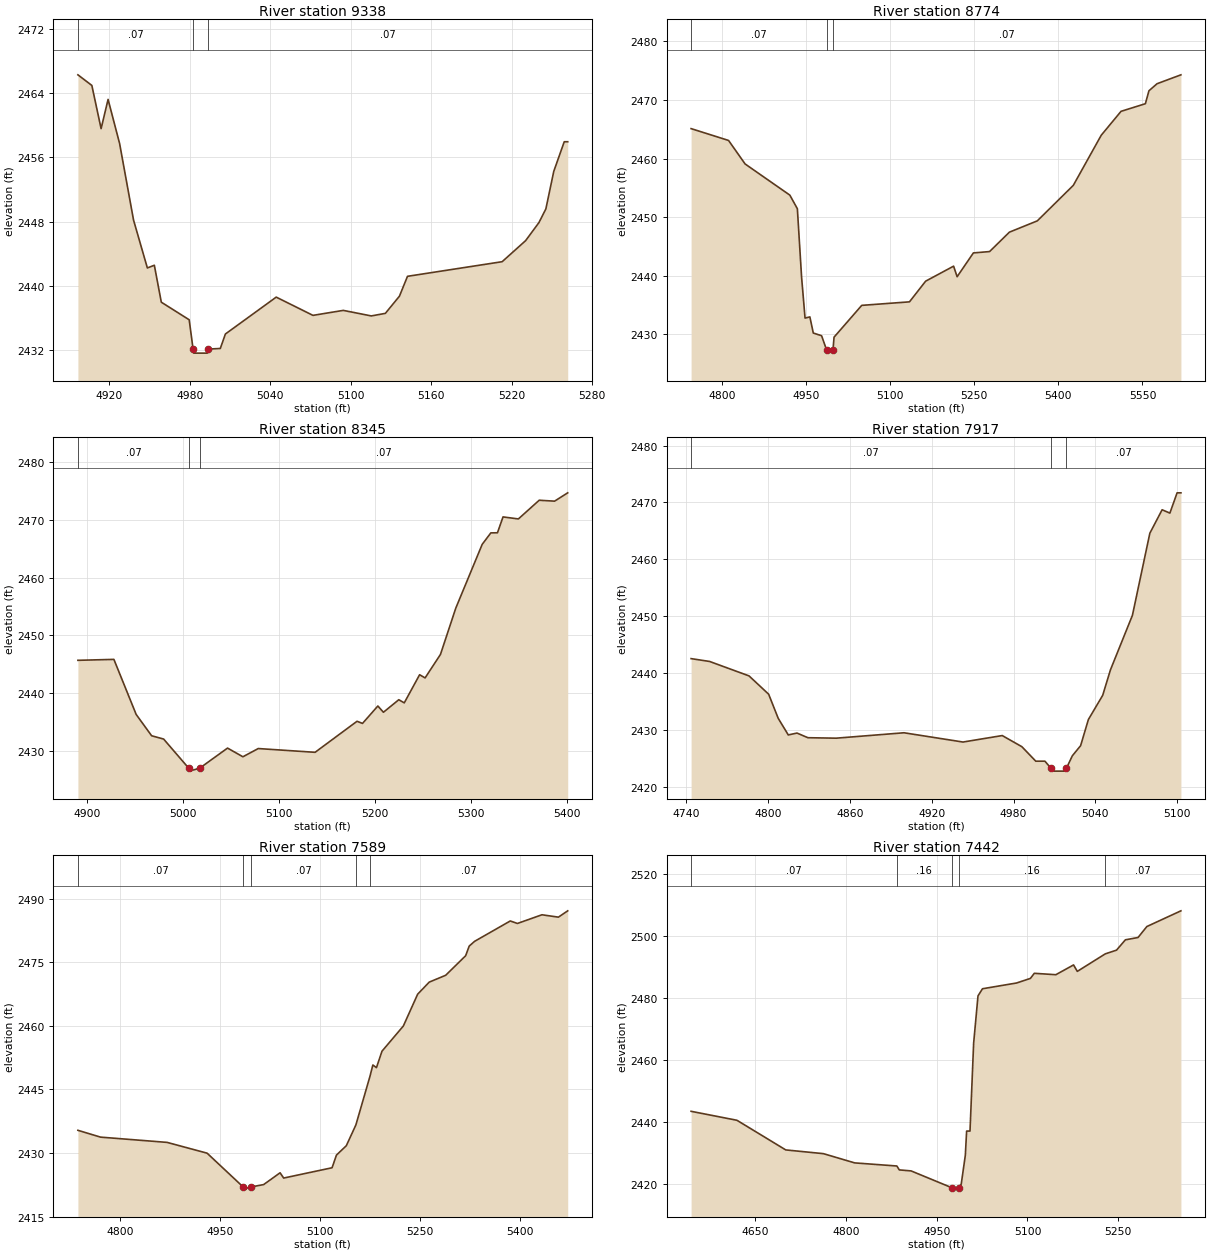
Type RM Length L Ch R = 1,9338,564,564,564
BEGIN DESCRIPTION:
Sweetwater Creek Trib 6 17.0
END DESCRIPTION:
XS GIS Cut Line= 3
      1363205.04      6796687.99      1363105.29      6796715.24
      1362855.04      6796638.01
#Sta/Elev= 30
  4896.6 2466.29  4907.0 2464.97  4913.9 2459.59  4919.1 2463.23  4927.7 2457.74
  4938.1 2448.21  4948.4 2442.25  4953.6 2442.59  4958.8 2437.99  4979.6 2435.80
  4982.5 2432.15  4983.0 2431.65  4993.2 2431.65  4993.7 2432.15  5002.8 2432.23
  5006.6 2434.03  5044.5 2438.62  5071.9 2436.35  5094.5 2436.97  5115.4 2436.28
  5125.9 2436.60  5136.4 2438.74  5142.4 2441.21  5213.0 2443.03  5230.5 2445.65
  5240.4 2447.89  5245.6 2449.60  5251.5 2454.28  5259.3 2457.96  5261.9 2457.96
#Mann=3,-1,0
  4896.6    0.07       0  4982.5    0.07       0  4993.7    0.07       0
Bank Sta=4982.5,4993.7
Exp/Cntr=0.3,0.1

Type RM Length L Ch R = 1,8774,429,429,429
BEGIN DESCRIPTION:
Sweetwater Creek Trib 6 4164
END DESCRIPTION:
XS GIS Cut Line= 3
      1363345.42      6796552.13      1363197.14      6796344.80
      1362708.96      6795964.86
#Sta/Elev= 30
  4745.1 2465.13  4811.9 2463.11  4841.4 2459.10  4921.2 2453.78  4934.6 2451.46
  4942.1 2439.82  4948.3 2432.80  4956.9 2433.00  4963.0 2430.25  4977.8 2429.79
  4986.9 2427.32  4987.4 2426.82  4998.1 2427.32  5000.0 2429.54  5049.4 2434.97
  5134.5 2435.57  5163.4 2439.10  5213.2 2441.66  5219.5 2439.86  5248.5 2443.92
  5277.4 2444.15  5312.7 2447.46  5362.5 2449.39  5426.7 2455.45  5476.5 2464.00
  5511.8 2468.08  5555.2 2469.38  5561.6 2471.59  5576.0 2472.79  5618.6 2474.31
#Mann=3,-1,0
  4745.1    0.07       0  4986.9    0.07       0  4998.1    0.07       0
Bank Sta=4986.9,4998.1
Exp/Cntr=0.3,0.1

Type RM Length L Ch R = 1,8345,428,428,428
BEGIN DESCRIPTION:
Sweetwater Creek Trib 6 16.0
END DESCRIPTION:
XS GIS Cut Line= 3
      1363355.04      6795887.98      1363255.09      6795932.96
      1362905.02      6795738.01
#Sta/Elev= 30
  4890.4 2445.70  4927.9 2445.86  4951.1 2436.35  4967.2 2432.67  4979.7 2432.10
  5005.9 2427.06  5006.4 2426.56  5017.2 2427.06  5046.3 2430.54  5062.3 2429.04
  5078.3 2430.46  5137.5 2429.81  5181.2 2435.17  5186.9 2434.80  5202.9 2437.81
  5208.7 2436.73  5224.7 2438.89  5230.4 2438.35  5246.4 2443.21  5252.1 2442.66
  5268.1 2446.71  5284.1 2454.72  5311.6 2465.73  5320.6 2467.71  5327.5 2467.73
  5333.3 2470.47  5349.3 2470.12  5371.0 2473.35  5387.0 2473.19  5400.7 2474.63
#Mann=3,-1,0
  4890.4    0.07       0  5005.9    0.07       0  5017.2    0.07       0
Bank Sta=5005.9,5017.2
Exp/Cntr=0.3,0.1

Type RM Length L Ch R = 1,7917,328,328,328
BEGIN DESCRIPTION:
Sweetwater Creek Trib 6 15.0
END DESCRIPTION:
XS GIS Cut Line= 3
      1363305.03      6795738.02      1363104.25      6795578.24
      1363055.00      6795488.00
#Sta/Elev= 30
  4743.4 2442.51  4757.0 2442.01  4785.9 2439.47  4800.3 2436.25  4807.3 2432.01
  4814.7 2429.08  4821.1 2429.41  4829.1 2428.59  4849.9 2428.51  4899.6 2429.46
  4942.9 2427.83  4971.7 2428.97  4986.1 2427.01  4996.3 2424.46  5003.0 2424.46
  5007.5 2423.21  5008.0 2422.71  5018.3 2422.71  5018.8 2423.21  5023.1 2425.40
  5029.2 2427.19  5034.9 2431.79  5045.4 2436.05  5051.1 2440.54  5067.2 2450.12
  5080.0 2464.58  5089.0 2468.71  5094.7 2468.12  5100.0 2471.69  5102.8 2471.69
#Mann=3,-1,0
  4743.4    0.07       0  5007.5    0.07       0  5018.8    0.07       0
Bank Sta=5007.5,5018.8
Exp/Cntr=0.3,0.1

Type RM Length L Ch R = 1,7589,147,147,147
BEGIN DESCRIPTION:
Sweetwater Creek Trib 6 4163
END DESCRIPTION:
XS GIS Cut Line= 3
      1363350.90      6795662.01      1363345.20      6795398.47
      1363175.95      6794957.43
#Sta/Elev= 30
  4736.4 2435.36  4770.4 2433.75  4870.4 2432.51  4930.5 2429.97  4984.8 2421.99
  4985.3 2421.49  4996.1 2421.99  5015.5 2422.56  5040.2 2425.34  5045.6 2424.10
  5118.3 2426.53  5124.9 2429.52  5139.7 2431.72  5154.1 2436.63  5175.2 2448.06
  5179.6 2450.76  5185.0 2450.13  5193.3 2454.01  5225.4 2459.95  5246.9 2467.45
  5264.3 2470.30  5289.0 2471.91  5319.0 2476.52  5324.4 2478.80  5332.5 2479.92
  5386.1 2484.72  5396.8 2484.13  5433.7 2486.18  5458.4 2485.62  5472.4 2487.11
#Mann=5,-1,0
  4736.4    0.07       0  4984.8    0.07       0  4996.1    0.07       0
  5154.1    0.16       0  5175.2    0.07       0
Bank Sta=4984.8,4996.1
Exp/Cntr=0.3,0.1

Type RM Length L Ch R = 1,7442,498,498,498
BEGIN DESCRIPTION:
Sweetwater Creek Trib 6 14.0
END DESCRIPTION:
XS GIS Cut Line= 3
      1363370.97      6795829.07      1363490.31      6795388.86
      1363775.80      6795180.06
#Sta/Elev= 30
  4543.9 2443.50  4619.7 2440.61  4700.4 2431.06  4762.6 2429.86  4814.4 2426.88
  4884.1 2425.88  4888.1 2424.62  4907.6 2424.30  4974.4 2418.93  4974.9 2418.43
  4986.0 2418.93  4990.5 2420.03  4997.3 2429.38  4999.4 2437.13  5005.0 2437.13
  5011.0 2465.43  5018.2 2480.67  5025.6 2482.98  5082.0 2484.84  5104.9 2486.32
  5111.3 2487.96  5146.9 2487.51  5176.2 2490.66  5182.4 2488.58  5228.7 2494.23
  5247.2 2495.42  5261.9 2498.75  5282.8 2499.50  5297.4 2503.03  5353.7 2508.09
#Mann=5,-1,0
  4543.9    0.07       0  4884.1    0.16       0  4974.4    0.07       0
  4986.0    0.16       0  5228.7    0.07       0
Bank Sta=4974.4,4986
Exp/Cntr=0.3,0.1

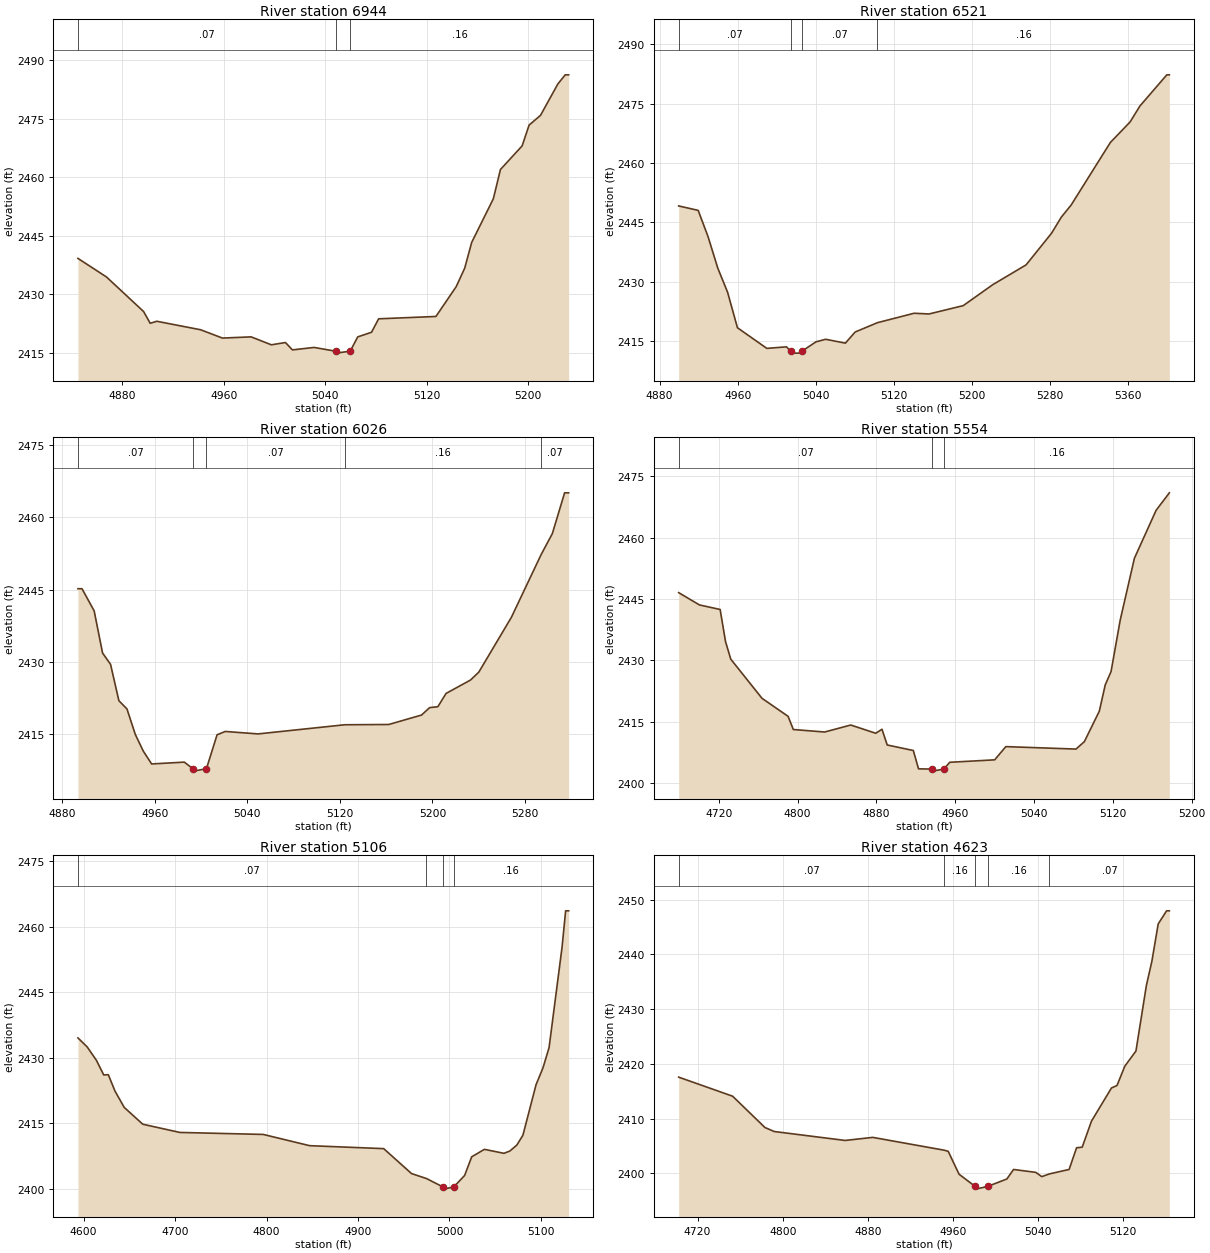
Type RM Length L Ch R = 1,6944,423,423,423
BEGIN DESCRIPTION:
Sweetwater Creek Trib 6 13.0
END DESCRIPTION:
XS GIS Cut Line= 3
      1363455.00      6795888.00      1363604.55      6795847.28
      1363704.99      6795638.03
#Sta/Elev= 30
  4845.0 2439.25  4867.5 2434.49  4896.8 2425.62  4902.0 2422.61  4907.2 2423.13
  4941.8 2420.95  4959.0 2418.82  4981.6 2419.13  4997.6 2417.09  5008.7 2417.68
  5014.2 2415.79  5031.3 2416.42  5048.2 2415.46  5048.7 2414.96  5059.8 2415.46
  5065.7 2419.12  5076.6 2420.31  5082.2 2423.76  5127.4 2424.36  5143.4 2432.01
  5150.1 2436.75  5155.6 2443.34  5172.7 2454.55  5178.3 2462.05  5195.4 2468.10
  5200.9 2473.43  5209.9 2475.93  5223.6 2483.99  5229.4 2486.32  5232.1 2486.32
#Mann=3,-1,0
  4845.0    0.07       0  5048.2    0.07       0  5059.8    0.16       0
Bank Sta=5048.2,5059.8
Exp/Cntr=0.3,0.1

Type RM Length L Ch R = 1,6521,495,495,495
BEGIN DESCRIPTION:
Sweetwater Creek Trib 6 12.0
END DESCRIPTION:
XS GIS Cut Line= 3
      1363805.00      6796237.96      1363814.14      6796137.88
      1363855.00      6795737.96
#Sta/Elev= 30
  4899.5 2449.18  4919.5 2448.06  4929.6 2441.43  4939.6 2433.46  4949.6 2427.39
  4959.7 2418.42  4989.8 2413.21  5009.9 2413.60  5014.2 2412.51  5014.7 2412.01
  5025.3 2412.01  5025.8 2412.51  5040.1 2414.86  5050.1 2415.51  5070.2 2414.53
  5080.3 2417.35  5103.1 2419.70  5140.6 2422.08  5155.9 2421.90  5190.9 2424.00
  5221.0 2429.27  5255.3 2434.30  5281.3 2442.27  5291.4 2446.36  5301.4 2449.40
  5341.6 2465.21  5361.8 2470.39  5371.8 2474.40  5399.4 2482.29  5402.0 2482.29
#Mann=4,-1,0
  4899.5    0.07       0  5014.2    0.07       0  5025.8    0.07       0
  5103.1    0.16       0
Bank Sta=5014.2,5025.8
Exp/Cntr=0.3,0.1

Type RM Length L Ch R = 1,6026,472,472,472
BEGIN DESCRIPTION:
Sweetwater Creek Trib 6 11.0
END DESCRIPTION:
XS GIS Cut Line= 3
      1364154.97      6796438.03      1364228.70      6796361.18
      1364454.97      6796138.03
#Sta/Elev= 30
  4893.5 2445.19  4897.0 2445.19  4907.5 2440.60  4914.8 2431.83  4921.7 2429.48
  4928.9 2421.93  4935.9 2420.21  4943.1 2414.92  4950.0 2411.46  4957.2 2408.79
  4985.5 2409.17  4992.9 2407.80  4993.4 2407.30  5004.6 2407.80  5013.8 2414.85
  5020.9 2415.54  5049.2 2415.03  5124.2 2416.93  5162.3 2416.99  5190.6 2418.95
  5197.6 2420.49  5204.7 2420.68  5211.8 2423.44  5233.0 2426.23  5240.1 2427.86
  5268.3 2439.26  5294.0 2452.28  5303.7 2456.64  5314.3 2465.11  5317.8 2465.11
#Mann=5,-1,0
  4893.5    0.07       0  4992.9    0.07       0  5004.6    0.07       0
  5124.2    0.16       0  5294.0    0.07       0
Bank Sta=4992.9,5004.6
Exp/Cntr=0.3,0.1

Type RM Length L Ch R = 1,5554,448,448,448
BEGIN DESCRIPTION:
Sweetwater Creek Trib 6 10.0
END DESCRIPTION:
XS GIS Cut Line= 3
      1364305.05      6796637.98      1364609.73      6796537.57
      1364704.98      6796388.03
#Sta/Elev= 30
  4679.2 2446.54  4700.3 2443.53  4721.3 2442.42  4726.8 2434.55  4732.1 2430.28
  4763.8 2420.71  4790.3 2416.30  4795.6 2413.08  4827.4 2412.47  4853.9 2414.18
  4879.2 2412.17  4885.6 2413.14  4890.9 2409.30  4917.4 2407.95  4922.7 2403.47
  4936.5 2403.41  4937.0 2402.91  4948.3 2403.41  4954.4 2405.07  5000.0 2405.67
  5011.3 2408.90  5082.5 2408.30  5091.0 2410.11  5106.2 2417.56  5112.2 2423.98
  5118.1 2427.23  5127.4 2439.82  5141.8 2454.92  5163.8 2466.64  5177.3 2470.93
#Mann=3,-1,0
  4679.2    0.07       0  4936.5    0.07       0  4948.3    0.16       0
Bank Sta=4936.5,4948.3
Exp/Cntr=0.3,0.1

Type RM Length L Ch R = 1,5106,483,483,483
BEGIN DESCRIPTION:
Sweetwater Creek Trib 6 9.0
END DESCRIPTION:
XS GIS Cut Line= 3
      1364505.04      6796887.99      1364905.94      6796822.61
      1365005.02      6796737.98
#Sta/Elev= 30
  4593.8 2434.53  4603.9 2432.47  4614.0 2429.40  4622.0 2426.05  4627.0 2426.11
  4634.3 2422.36  4644.4 2418.62  4664.7 2414.77  4705.2 2412.89  4796.4 2412.43
  4847.1 2409.86  4928.1 2409.18  4958.5 2403.47  4974.8 2402.34  4992.9 2400.41
  4993.4 2399.91  5004.7 2400.41  5016.6 2403.05  5024.3 2407.31  5038.2 2409.02
  5059.5 2408.11  5066.0 2408.63  5073.7 2410.01  5080.3 2412.25  5094.6 2423.79
  5102.3 2427.72  5108.9 2432.33  5123.1 2455.32  5127.0 2463.63  5130.3 2463.63
#Mann=4,-1,0
  4593.8    0.07       0  4974.8    0.16       0  4992.9    0.07       0
  5004.7    0.16       0
Bank Sta=4992.9,5004.7
Exp/Cntr=0.3,0.1

Type RM Length L Ch R = 1,4623,498,498,498
BEGIN DESCRIPTION:
Sweetwater Creek Trib 6 8.0
END DESCRIPTION:
XS GIS Cut Line= 3
      1364754.95      6797187.99      1365048.89      6797235.82
      1365205.03      6797187.99
#Sta/Elev= 30
  4702.2 2417.59  4752.9 2414.11  4783.3 2408.39  4792.0 2407.66  4858.6 2406.03
  4884.6 2406.59  4951.7 2404.25  4955.5 2404.04  4965.7 2399.86  4980.8 2397.64
  4981.3 2397.14  4992.6 2397.64  5010.6 2398.99  5016.9 2400.73  5037.8 2400.20
  5043.4 2399.42  5050.6 2399.92  5069.1 2400.73  5076.1 2404.69  5081.4 2404.80
  5090.1 2409.55  5108.9 2415.61  5114.1 2416.06  5121.4 2419.58  5131.9 2422.36
  5141.7 2434.32  5146.9 2438.78  5152.8 2445.56  5160.7 2447.96  5163.3 2447.96
#Mann=5,-1,0
  4702.2    0.07       0  4951.7    0.16       0  4980.8    0.07       0
  4992.6    0.16       0  5050.6    0.07       0
Bank Sta=4980.8,4992.6
Exp/Cntr=0.3,0.1

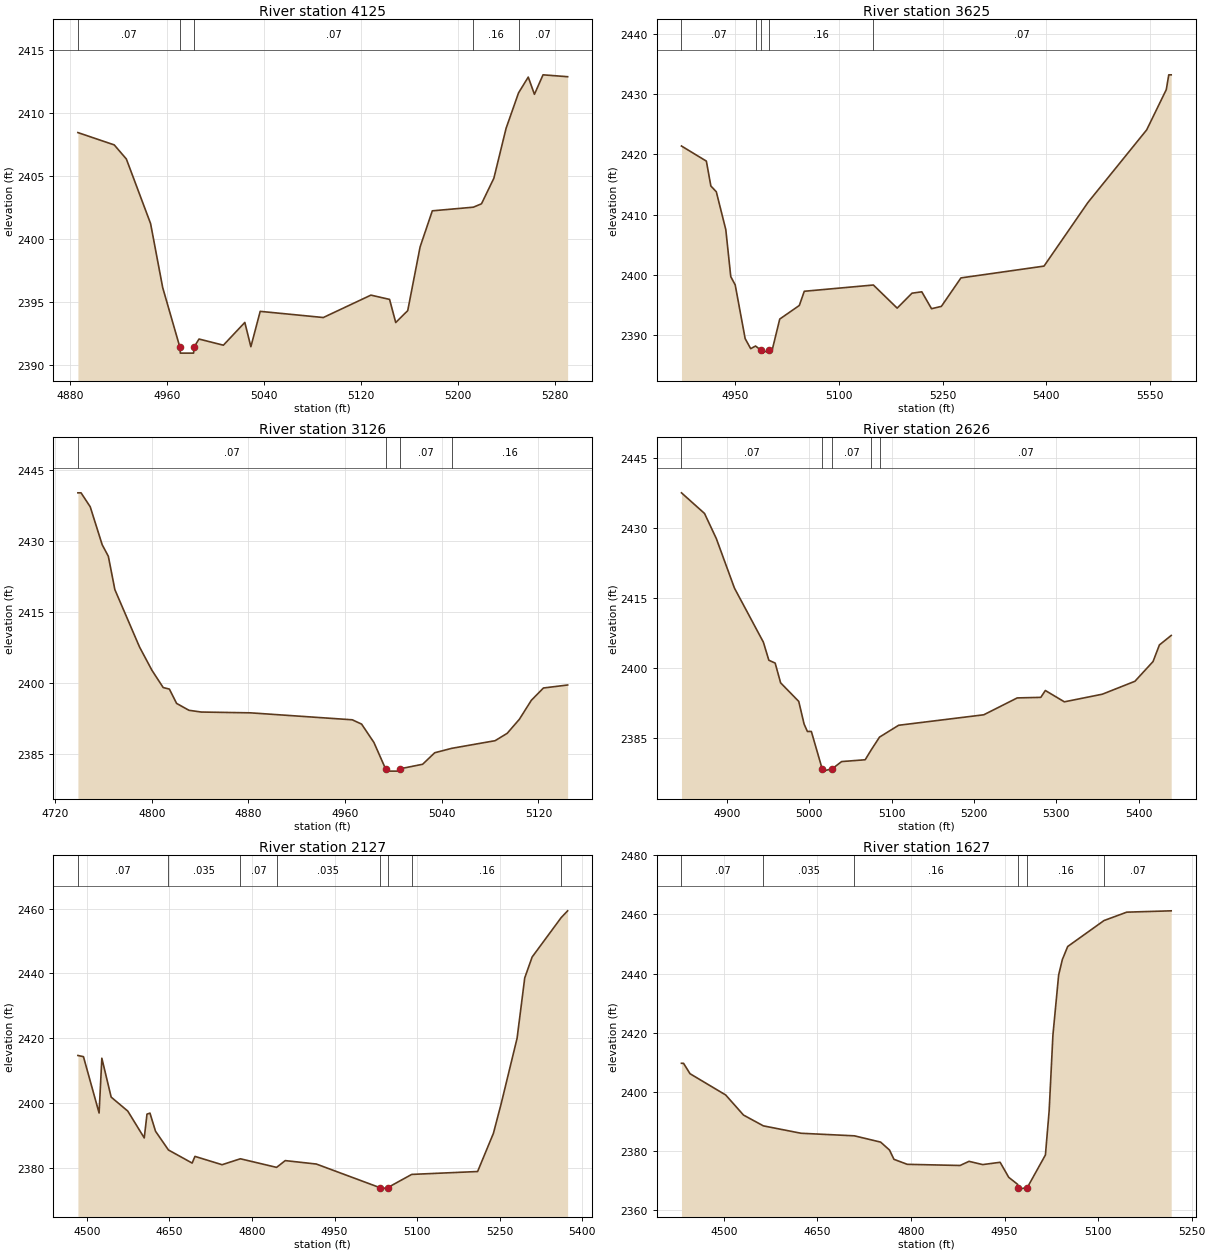
Type RM Length L Ch R = 1,4125,500,500,500
BEGIN DESCRIPTION:
Sweetwater Creek Trib 6 7.0
END DESCRIPTION:
XS GIS Cut Line= 3
      1364805.00      6797538.00      1364918.69      6797538.48
      1365205.04      6797588.01
#Sta/Elev= 30
  4886.3 2408.45  4916.3 2407.47  4926.3 2406.35  4946.3 2401.22  4956.3 2396.13
  4970.4 2391.42  4970.9 2390.92  4981.8 2390.92  4982.3 2391.42  4986.3 2392.04
  5006.4 2391.55  5024.1 2393.36  5029.1 2391.43  5036.8 2394.24  5088.9 2393.75
  5128.2 2395.53  5143.6 2395.19  5148.7 2393.35  5158.6 2394.30  5168.8 2399.36
  5178.9 2402.23  5212.8 2402.52  5219.5 2402.79  5229.7 2404.82  5239.8 2408.79
  5250.1 2411.61  5258.1 2412.86  5263.2 2411.49  5270.3 2413.04  5290.6 2412.89
#Mann=5,-1,0
  4886.3    0.07       0  4970.4    0.07       0  4982.3    0.07       0
  5212.8    0.16       0  5250.1    0.07       0
Bank Sta=4970.4,4982.3
Exp/Cntr=0.3,0.1

Type RM Length L Ch R = 1,3625,499,499,499
BEGIN DESCRIPTION:
Sweetwater Creek Trib 6 6.0
END DESCRIPTION:
XS GIS Cut Line= 3
      1364804.97      6798038.02      1364904.46      6797958.29
      1365305.02      6797537.98
#Sta/Elev= 30
  4872.5 2421.40  4908.5 2418.89  4915.0 2414.76  4922.9 2413.79  4936.6 2407.50
  4943.8 2399.69  4950.2 2398.32  4964.6 2389.39  4972.6 2387.72  4979.6 2388.16
  4987.3 2387.48  4987.8 2386.98  4999.4 2387.48  5003.7 2387.51  5014.6 2392.64
  5042.9 2394.90  5050.1 2397.26  5150.0 2398.30  5184.4 2394.46  5205.8 2396.94
  5220.0 2397.17  5234.1 2394.36  5248.3 2394.75  5276.6 2399.48  5396.7 2401.44
  5460.3 2412.03  5545.2 2424.09  5573.5 2430.77  5577.1 2433.23  5580.6 2433.23
#Mann=5,-1,0
  4872.5    0.07       0  4979.6    0.16       0  4987.3    0.07       0
  4999.4    0.16       0  5150.0    0.07       0
Bank Sta=4987.3,4999.4
Exp/Cntr=0.3,0.1

Type RM Length L Ch R = 1,3126,500,500,500
BEGIN DESCRIPTION:
Sweetwater Creek Trib 6 5.0
END DESCRIPTION:
XS GIS Cut Line= 3
      1365305.00      6798288.01      1365357.35      6798032.22
      1365355.00      6797888.03
#Sta/Elev= 30
  4738.9 2440.10  4741.5 2440.10  4749.1 2437.15  4759.0 2429.14  4764.1 2426.69
  4769.5 2419.65  4789.9 2407.54  4800.2 2402.61  4809.5 2398.97  4814.6 2398.65
  4820.6 2395.62  4830.8 2394.17  4841.0 2393.80  4881.8 2393.63  4966.0 2392.16
  4973.7 2391.25  4983.9 2387.37  4993.5 2381.82  4994.0 2381.32  5005.1 2381.32
  5005.6 2381.82  5024.2 2382.77  5034.2 2385.20  5048.2 2386.13  5084.2 2387.75
  5094.2 2389.31  5104.2 2392.25  5114.2 2396.29  5124.2 2398.88  5144.2 2399.51
#Mann=4,-1,0
  4738.9    0.07       0  4993.5    0.07       0  5005.6    0.07       0
  5048.2    0.16       0
Bank Sta=4993.5,5005.6
Exp/Cntr=0.3,0.1

Type RM Length L Ch R = 1,2626,499,499,499
BEGIN DESCRIPTION:
Sweetwater Creek Trib 6 4.0
END DESCRIPTION:
XS GIS Cut Line= 3
      1365655.00      6798288.00      1365773.22      6798187.91
      1365955.01      6797787.98
#Sta/Elev= 30
  4845.1 2437.52  4873.1 2433.09  4887.4 2427.70  4909.4 2417.07  4944.5 2405.47
  4951.1 2401.60  4958.8 2400.98  4965.4 2396.75  4987.4 2392.76  4993.9 2387.90
  4997.9 2386.31  5002.7 2386.31  5015.8 2378.30  5016.3 2377.80  5028.0 2378.30
  5039.4 2379.85  5068.0 2380.24  5075.4 2382.38  5085.4 2385.10  5108.6 2387.64
  5211.9 2389.89  5252.5 2393.51  5281.1 2393.63  5286.6 2395.10  5309.7 2392.67
  5355.8 2394.31  5395.3 2397.08  5417.3 2401.32  5425.0 2404.88  5439.3 2406.91
#Mann=5,-1,0
  4845.1    0.07       0  5015.8    0.07       0  5028.0    0.07       0
  5075.4    0.16       0  5085.4    0.07       0
Bank Sta=5015.8,5028
Exp/Cntr=0.3,0.1

Type RM Length L Ch R = 1,2127,500,500,500
BEGIN DESCRIPTION:
Sweetwater Creek Trib 6 3.0
END DESCRIPTION:
XS GIS Cut Line= 3
      1366205.00      6798687.99      1366266.85      6798175.61
      1366504.99      6797888.01
#Sta/Elev= 30
  4483.9 2414.71  4494.0 2414.34  4522.4 2396.96  4527.4 2413.86  4544.3 2401.87
  4574.5 2397.55  4604.4 2389.28  4609.4 2396.61  4614.8 2396.92  4624.9 2391.33
  4648.4 2385.55  4691.4 2381.52  4696.5 2383.58  4745.8 2381.01  4779.0 2382.84
  4844.8 2380.19  4860.5 2382.28  4917.0 2381.22  5031.7 2373.98  5032.2 2373.48
  5047.0 2373.98  5090.2 2378.02  5209.9 2378.91  5238.6 2390.69  5252.9 2399.97
  5281.6 2420.01  5295.5 2438.64  5308.9 2445.07  5361.7 2457.24  5373.4 2459.33
#Mann=8,-1,0
  4483.9    0.07       0  4648.4   0.035       0  4779.0    0.07       0
  4844.8   0.035       0  5031.7   0.035       0  5047.0   0.035       0
  5090.2    0.16       0  5361.7    0.07       0
Bank Sta=5031.7,5047
Exp/Cntr=0.3,0.1

Type RM Length L Ch R = 1,1627,499,499,499
BEGIN DESCRIPTION:
Sweetwater Creek Trib 6 2.0
END DESCRIPTION:
XS GIS Cut Line= 3
      1366255.00      6798588.00      1366688.56      6798221.21
      1366805.01      6798037.99
#Sta/Elev= 30
  4432.1 2409.66  4435.4 2409.66  4445.8 2406.14  4503.0 2398.94  4531.5 2392.15
  4563.4 2388.49  4623.8 2385.99  4709.3 2385.12  4751.3 2383.00  4765.6 2380.31
  4772.7 2377.17  4794.1 2375.48  4878.7 2375.09  4893.0 2376.49  4915.0 2375.39
  4942.9 2376.17  4956.7 2371.08  4971.0 2368.70  4971.1 2367.59  4971.6 2367.09
  4986.4 2367.59  5015.5 2378.65  5021.5 2393.64  5027.5 2419.14  5036.7 2439.52
  5042.6 2444.74  5051.2 2449.17  5109.4 2457.95  5145.9 2460.79  5217.1 2461.24
#Mann=6,-1,0
  4432.1    0.07       0  4563.4   0.035       0  4709.3    0.16       0
  4971.1    0.07       0  4986.4    0.16       0  5109.4    0.07       0
Bank Sta=4971.1,4986.4
Exp/Cntr=0.3,0.1

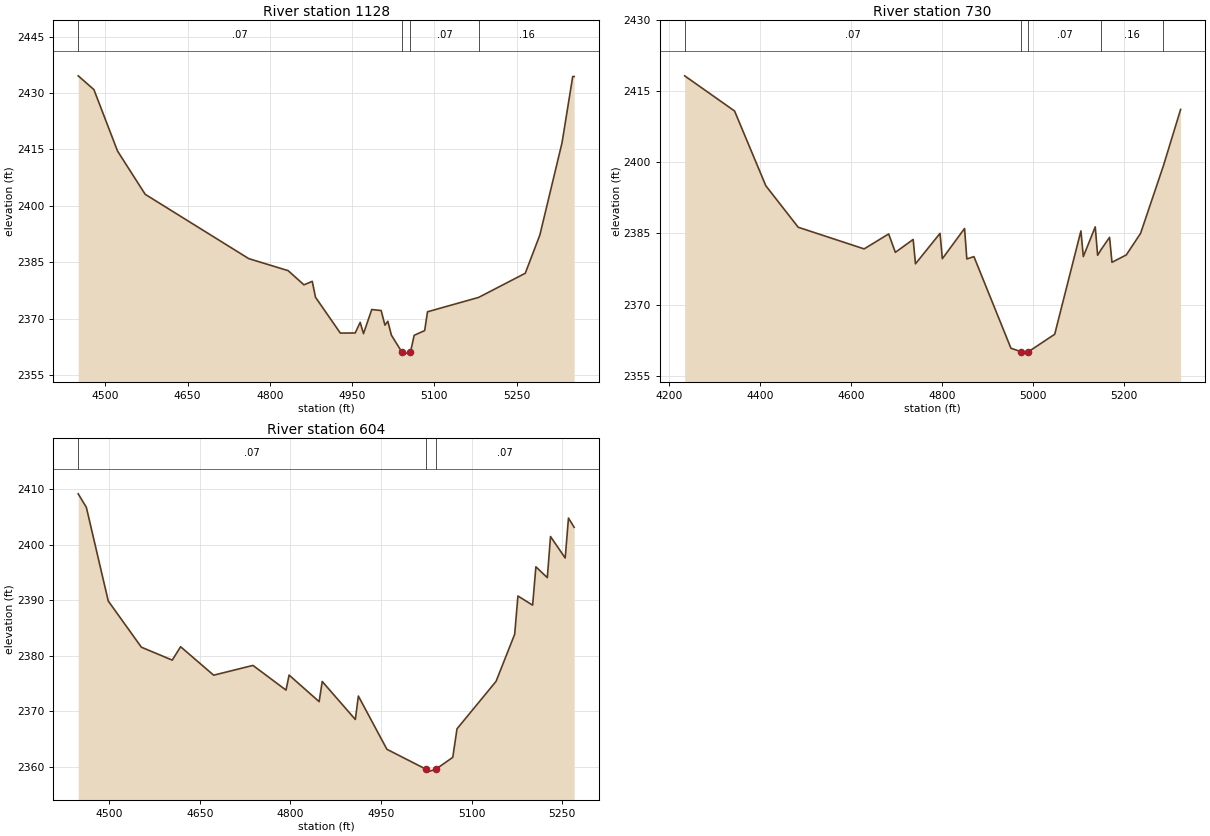
Type RM Length L Ch R = 1,1128,398,398,398
BEGIN DESCRIPTION:
Sweetwater Creek Trib 6 1.0
END DESCRIPTION:
XS GIS Cut Line= 3
      1366505.00      6799138.00      1366806.14      6798678.61
      1366905.01      6798337.97
#Sta/Elev= 30
  4450.7 2434.58  4479.3 2430.92  4522.4 2414.56  4572.8 2403.05  4761.6 2385.93
  4833.3 2382.74  4862.2 2378.96  4877.3 2379.89  4883.2 2375.66  4928.5 2366.12
  4955.6 2366.15  4964.7 2368.98  4970.7 2365.97  4985.8 2372.39  5002.9 2372.12
  5009.8 2368.23  5015.1 2369.27  5021.5 2365.59  5040.9 2361.02  5041.4 2360.52
  5056.3 2361.02  5063.1 2365.53  5082.2 2366.78  5087.4 2371.79  5180.7 2375.62
  5265.6 2382.04  5292.2 2392.22  5332.7 2416.83  5352.1 2434.40  5354.7 2434.40
#Mann=4,-1,0
  4450.7    0.07       0  5040.9    0.07       0  5056.3    0.07       0
  5180.7    0.16       0
Bank Sta=5040.9,5056.3
Exp/Cntr=0.3,0.1

Type RM Length L Ch R = 1,730,126,126,126
BEGIN DESCRIPTION:
Sweetwater Creek Trib 6 4162
END DESCRIPTION:
XS GIS Cut Line= 3
      1367278.76      6799493.57      1367144.31      6798739.67
      1367040.73      6798433.09
#Sta/Elev= 30
  4234.2 2418.27  4343.8 2410.85  4412.5 2395.06  4483.6 2386.31  4628.4 2381.74
  4682.3 2384.90  4697.0 2381.01  4736.1 2383.73  4741.2 2378.59  4795.1 2385.02
  4800.2 2379.67  4849.0 2386.05  4854.0 2379.62  4869.6 2380.11  4950.9 2360.77
  4973.7 2360.03  4974.2 2359.53  4989.1 2360.03  5047.0 2363.72  5104.6 2385.53
  5109.9 2380.13  5136.1 2386.39  5141.3 2380.39  5148.8 2381.58  5167.5 2384.18
  5172.8 2378.91  5204.3 2380.47  5235.7 2385.03  5285.8 2399.29  5323.6 2411.18
#Mann=5,-1,0
  4234.2    0.07       0  4973.7    0.07       0  4989.1    0.07       0
  5148.8    0.16       0  5285.8    0.07       0
Bank Sta=4973.7,4989.1
Exp/Cntr=0.3,0.1

Type RM Length L Ch R = 1,604,0,0,0
BEGIN DESCRIPTION:
Sweetwater Creek Trib 6 2062
END DESCRIPTION:
XS GIS Cut Line= 3
      1367348.56      6799331.31      1367254.87      6798788.33
      1367155.01      6798538.01
#Sta/Elev= 30
  4449.0 2409.16  4462.5 2406.72  4498.7 2389.88  4553.5 2381.57  4604.6 2379.24
  4618.4 2381.65  4673.1 2376.53  4738.1 2378.29  4792.8 2373.85  4797.9 2376.55
  4847.6 2371.77  4852.7 2375.40  4907.5 2368.56  4912.5 2372.78  4959.7 2363.20
  5024.9 2359.59  5025.4 2359.09  5040.4 2359.59  5068.7 2361.75  5075.7 2366.88
  5140.3 2375.42  5171.1 2383.89  5176.5 2390.78  5200.8 2389.13  5206.2 2396.03
  5225.1 2394.08  5230.4 2401.48  5254.7 2397.61  5260.1 2404.80  5269.5 2403.14
#Mann=3,-1,0
  4449.0    0.07       0  5024.9    0.07       0  5040.4    0.07       0
Bank Sta=5024.9,5040.4
Exp/Cntr=0.3,0.1

Chan Stop Cuts=-1