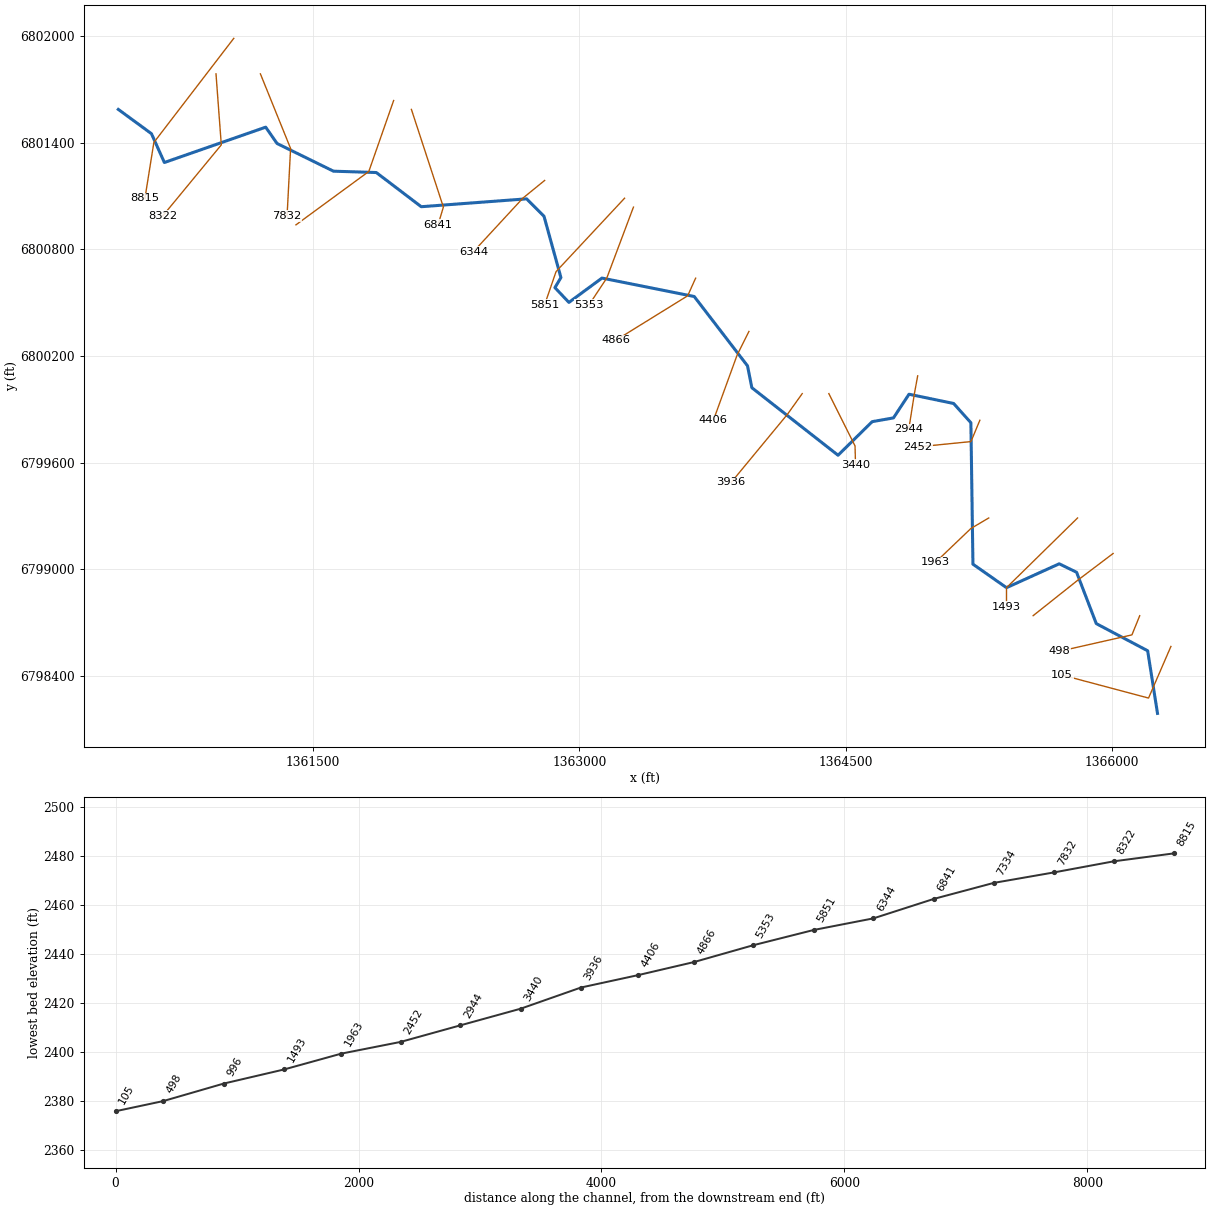
--- Sweetwater Creek Trib 6 T.prj (project) ---

Proj Title=Sweetwater Creek Trib 6 T Base Level Engineering
Current Plan=p01
Default Exp/Contr=0.3,0.1
English Units
Geom File=g01
Flow File=f01
Plan File=p01
BEGIN DESCRIPTION:
Sweetwater Creek Trib 6 T
END DESCRIPTION:

--- Sweetwater Creek Trib 6 T.p01 (plan) ---

Plan Title=Multiple Run
Short Identifier=Multiple
Geom File=g01
Flow File=f01
Subcritical Flow
K Sum by GR= 0
Std Step Tol= 0.01
Critical Tol= 0.01
Num of Std Step Trials= 20
Max Error Tol= 0.3
Flow Tol Ratio= 0.001
Split Flow NTrial= 30
Split Flow Tol= 0.02
Split Flow Ratio= 0.02
Log Output Level= 0
Friction Slope Method= 1
Unsteady Friction Slope Method= 2
Unsteady Bridges Friction Slope Method= 1
Parabolic Critical Depth
Global Vel Dist=  1 , 1 , 1
Global Log Level= 0
CheckData=True
Encroach Param= -1, 0, 0, 0
BEGIN DESCRIPTION:
Multiple Run
END DESCRIPTION:

--- Sweetwater Creek Trib 6 T.f01 (steady flow) ---

Flow Title=Multiple
Number of Profiles=7
Profile Names=10-year,25-year,50-year,1pct_min,100-year,1pct_plu,500-year
River Rch & RM= Sweetwater Creek,Reach-1,8815
     274     389     486     302     603    1204     941
River Rch & RM= Sweetwater Creek,Reach-1,8322
     405     589     747     471     940    1875    1508
Boundary for River Rch & Prof#=Sweetwater Creek,Reach-1,1
Up Type=0
Dn Type=3
Dn Slope=0.005
Boundary for River Rch & Prof#=Sweetwater Creek,Reach-1,2
Up Type=0
Dn Type=3
Dn Slope=0.005
Boundary for River Rch & Prof#=Sweetwater Creek,Reach-1,3
Up Type=0
Dn Type=3
Dn Slope=0.005
Boundary for River Rch & Prof#=Sweetwater Creek,Reach-1,4
Up Type=0
Dn Type=3
Dn Slope=0.005
Boundary for River Rch & Prof#=Sweetwater Creek,Reach-1,5
Up Type=0
Dn Type=3
Dn Slope=0.005
Boundary for River Rch & Prof#=Sweetwater Creek,Reach-1,6
Up Type=0
Dn Type=3
Dn Slope=0.005
Boundary for River Rch & Prof#=Sweetwater Creek,Reach-1,7
Up Type=0
Dn Type=3
Dn Slope=0.005

--- Sweetwater Creek Trib 6 T.g01 (geometry) ---

Geom Title=Existing Conditions

River Reach=Sweetwater Creek,Reach-1
Reach XY= 30
      1360405.00      6801588.00      1360591.60      6801451.30
      1360664.46      6801289.02      1361234.80      6801487.97
      1361298.68      6801396.07      1361616.29      6801240.19
      1361857.45      6801232.53      1362110.45      6801040.17
      1362703.54      6801084.48      1362801.46      6800986.54
      1362896.71      6800641.22      1362862.99      6800584.63
      1362941.61      6800501.41      1363127.72      6800638.38
      1363646.99      6800534.77      1363947.14      6800144.17
      1363971.44      6800021.21      1364456.68      6799641.09
      1364648.81      6799830.14      1364768.65      6799851.26
      1364856.28      6799984.63      1365107.44      6799932.48
      1365204.47      6799824.15      1365216.10      6799027.92
      1365404.99      6798895.53      1365701.72      6799029.99
      1365799.41      6798982.45      1365910.44      6798693.25
      1366199.55      6798540.47      1366255.00      6798188.00

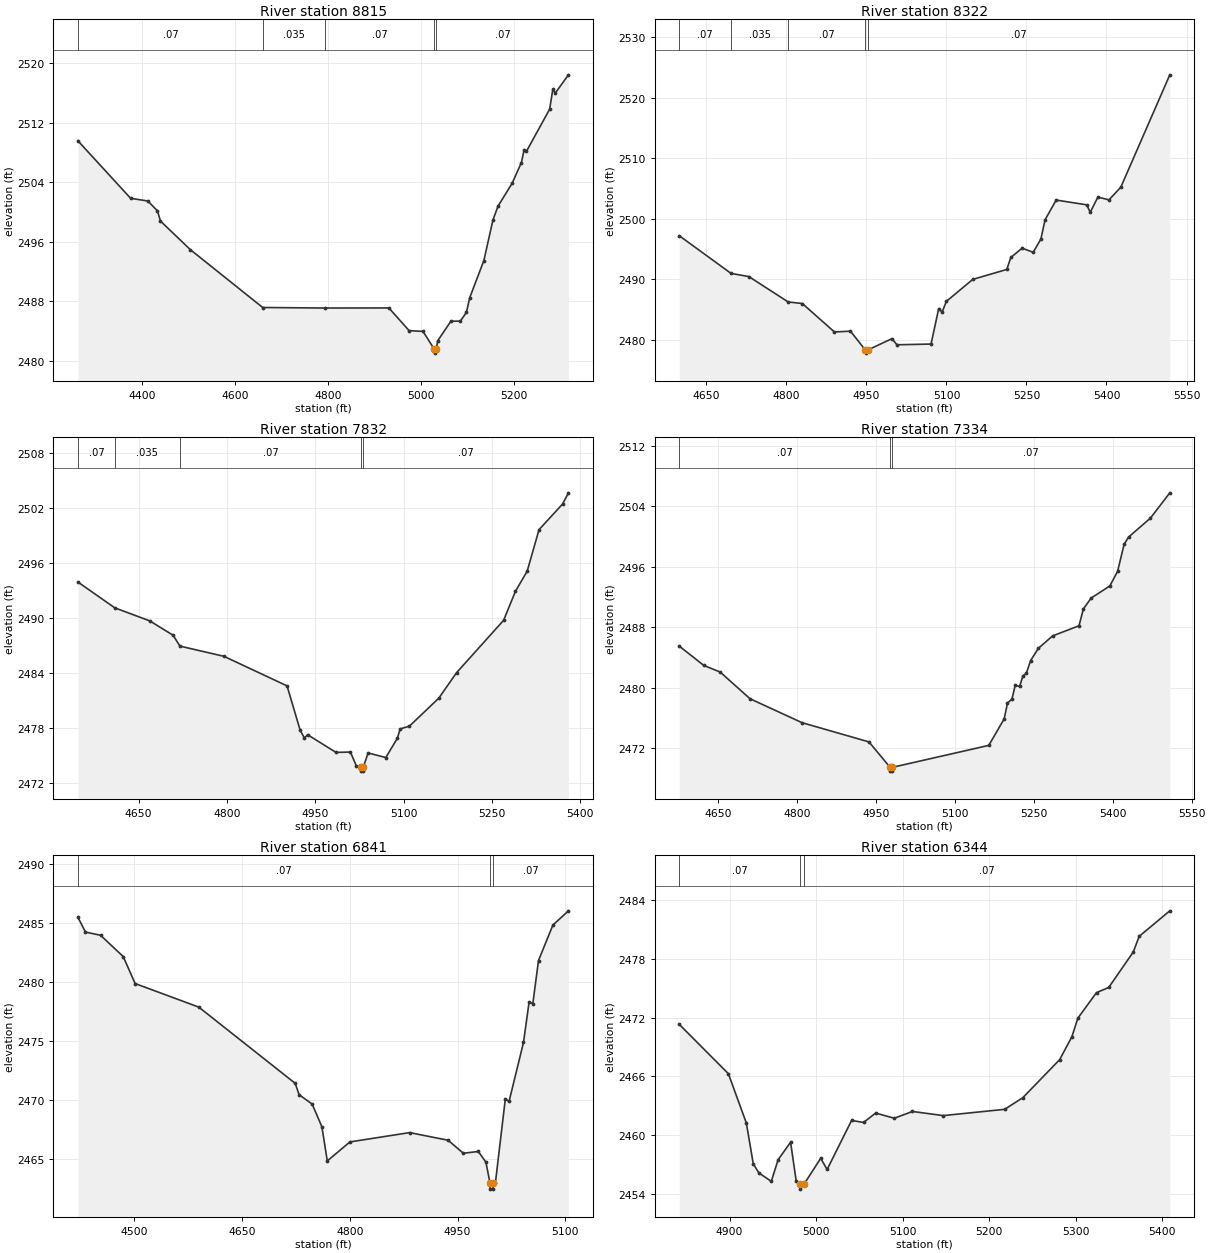
Type RM Length L Ch R = 1,8815,493,493,493
BEGIN DESCRIPTION:
Sweetwater Creek Trib 6 T 17.0
END DESCRIPTION:
XS GIS Cut Line= 3
      1361055.01      6801988.02      1360605.18      6801401.70
      1360555.00      6801087.99
#Sta/Elev= 30
  4261.0 2509.55  4374.5 2501.83  4411.5 2501.47  4432.3 2500.15  4438.7 2498.78
  4503.0 2494.94  4659.0 2487.16  4794.1 2487.09  4930.9 2487.10  4974.4 2484.05
  5004.4 2483.95  5028.9 2481.53  5029.2 2481.03  5032.9 2481.53  5036.0 2482.69
  5064.5 2485.32  5084.8 2485.33  5098.0 2486.51  5105.0 2488.48  5135.4 2493.45
  5155.0 2498.91  5165.8 2500.76  5196.2 2503.83  5216.4 2506.64  5222.1 2508.34
  5227.2 2508.14  5277.2 2513.81  5284.1 2516.50  5289.2 2515.96  5317.7 2518.42
#Mann=5,-1,0
  4261.0    0.07       0  4659.0   0.035       0  4794.1    0.07       0
  5028.9    0.07       0  5032.9    0.07       0
Bank Sta=5028.9,5032.9
Exp/Cntr=0.3,0.1

Type RM Length L Ch R = 1,8322,490,490,490
BEGIN DESCRIPTION:
Sweetwater Creek Trib 6 T 16.0
END DESCRIPTION:
XS GIS Cut Line= 3
      1360955.00      6801788.00      1360984.87      6801388.32
      1360655.01      6800988.01
#Sta/Elev= 30
  4599.2 2497.20  4696.2 2490.98  4729.6 2490.45  4803.3 2486.26  4829.8 2486.00
  4890.0 2481.30  4920.1 2481.43  4948.1 2478.30  4948.4 2477.80  4952.2 2478.30
  4997.7 2480.19  5007.3 2479.18  5071.1 2479.30  5085.5 2485.16  5091.9 2484.58
  5099.8 2486.35  5149.3 2489.99  5213.1 2491.63  5220.7 2493.61  5241.8 2495.15
  5262.6 2494.47  5277.0 2496.65  5284.9 2499.85  5305.7 2503.10  5363.0 2502.31
  5369.5 2501.08  5383.9 2503.59  5404.7 2503.13  5426.9 2505.24  5518.7 2523.80
#Mann=5,-1,0
  4599.2    0.07       0  4696.2   0.035       0  4803.3    0.07       0
  4948.1    0.07       0  4952.2    0.07       0
Bank Sta=4948.1,4952.2
Exp/Cntr=0.3,0.1

Type RM Length L Ch R = 1,7832,498,498,498
BEGIN DESCRIPTION:
Sweetwater Creek Trib 6 T 15.0
END DESCRIPTION:
XS GIS Cut Line= 3
      1361205.01      6801787.96      1361374.92      6801367.82
      1361355.00      6800988.04
#Sta/Elev= 30
  4546.8 2493.89  4609.4 2491.08  4668.8 2489.66  4708.6 2488.09  4720.1 2486.91
  4794.8 2485.80  4902.1 2482.58  4924.3 2477.77  4931.6 2476.89  4937.0 2477.26
  4985.3 2475.33  5009.8 2475.37  5019.8 2473.87  5027.8 2473.79  5028.1 2473.29
  5031.7 2473.29  5032.0 2473.79  5039.9 2475.27  5069.9 2474.77  5089.4 2476.85
  5094.4 2477.89  5110.0 2478.19  5160.0 2481.24  5190.1 2484.01  5270.2 2489.73
  5290.2 2492.88  5310.2 2495.08  5330.3 2499.60  5370.3 2502.39  5380.3 2503.61
#Mann=5,-1,0
  4546.8    0.07       0  4609.4   0.035       0  4720.1    0.07       0
  5027.8    0.07       0  5032.0    0.07       0
Bank Sta=5027.8,5032
Exp/Cntr=0.3,0.1

Type RM Length L Ch R = 1,7334,493,493,493
BEGIN DESCRIPTION:
Sweetwater Creek Trib 6 T 14.0
END DESCRIPTION:
XS GIS Cut Line= 3
      1361955.02      6801638.04      1361815.21      6801238.50
      1361405.00      6800938.00
#Sta/Elev= 30
  4576.7 2485.50  4623.3 2482.95  4654.3 2482.08  4711.1 2478.55  4809.8 2475.39
  4937.0 2472.85  4977.2 2469.49  4977.5 2468.99  4981.2 2468.99  4981.4 2469.49
  5164.6 2472.39  5193.9 2475.90  5200.1 2477.97  5208.6 2478.51  5214.8 2480.31
  5223.2 2480.18  5229.4 2481.55  5235.8 2481.89  5244.1 2483.60  5258.8 2485.21
  5285.8 2486.85  5336.0 2488.19  5344.4 2490.43  5359.1 2491.85  5394.6 2493.45
  5409.3 2495.38  5421.7 2498.95  5430.1 2499.90  5471.8 2502.42  5508.5 2505.75
#Mann=3,-1,0
  4576.7    0.07       0  4977.2    0.07       0  4981.4    0.07       0
Bank Sta=4977.2,4981.4
Exp/Cntr=0.3,0.1

Type RM Length L Ch R = 1,6841,497,497,497
BEGIN DESCRIPTION:
Sweetwater Creek Trib 6 T 13.0
END DESCRIPTION:
XS GIS Cut Line= 3
      1362055.01      6801587.96      1362234.96      6801038.05
      1362205.01      6800938.04
#Sta/Elev= 30
  4421.4 2485.49  4431.9 2484.24  4452.9 2483.97  4484.5 2482.16  4501.0 2479.88
  4589.7 2477.88  4724.0 2471.42  4729.3 2470.46  4747.5 2469.67  4761.1 2467.74
  4768.6 2464.85  4800.1 2466.46  4883.3 2467.25  4936.9 2466.60  4958.0 2465.50
  4978.9 2465.65  4989.5 2464.74  4995.2 2462.96  4995.5 2462.46  4999.3 2462.46
  4999.6 2462.96  5002.6 2462.96  5016.5 2470.10  5021.7 2469.89  5041.8 2474.89
  5049.6 2478.31  5054.8 2478.18  5062.7 2481.83  5082.7 2484.83  5104.4 2486.04
#Mann=3,-1,0
  4421.4    0.07       0  4995.2    0.07       0  4999.6    0.07       0
Bank Sta=4995.2,4999.6
Exp/Cntr=0.3,0.1

Type RM Length L Ch R = 1,6344,493,493,493
BEGIN DESCRIPTION:
Sweetwater Creek Trib 6 T 12.0
END DESCRIPTION:
XS GIS Cut Line= 3
      1362804.99      6801187.99      1362682.35      6801088.22
      1362405.02      6800788.02
#Sta/Elev= 30
  4841.9 2471.30  4898.6 2466.28  4919.4 2461.25  4927.4 2457.09  4933.8 2456.18
  4948.2 2455.31  4956.1 2457.52  4970.5 2459.30  4976.9 2455.39  4981.3 2455.02
  4981.6 2454.52  4986.0 2455.02  5005.3 2457.66  5012.7 2456.52  5041.0 2461.52
  5054.8 2461.31  5068.8 2462.27  5090.3 2461.74  5111.3 2462.43  5147.0 2462.01
  5217.9 2462.65  5238.9 2463.84  5281.4 2467.71  5295.6 2470.05  5302.4 2471.93
  5324.0 2474.54  5338.1 2475.06  5366.5 2478.68  5373.3 2480.27  5408.7 2482.87
#Mann=3,-1,0
  4841.9    0.07       0  4981.3    0.07       0  4986.0    0.07       0
Bank Sta=4981.3,4986
Exp/Cntr=0.3,0.1

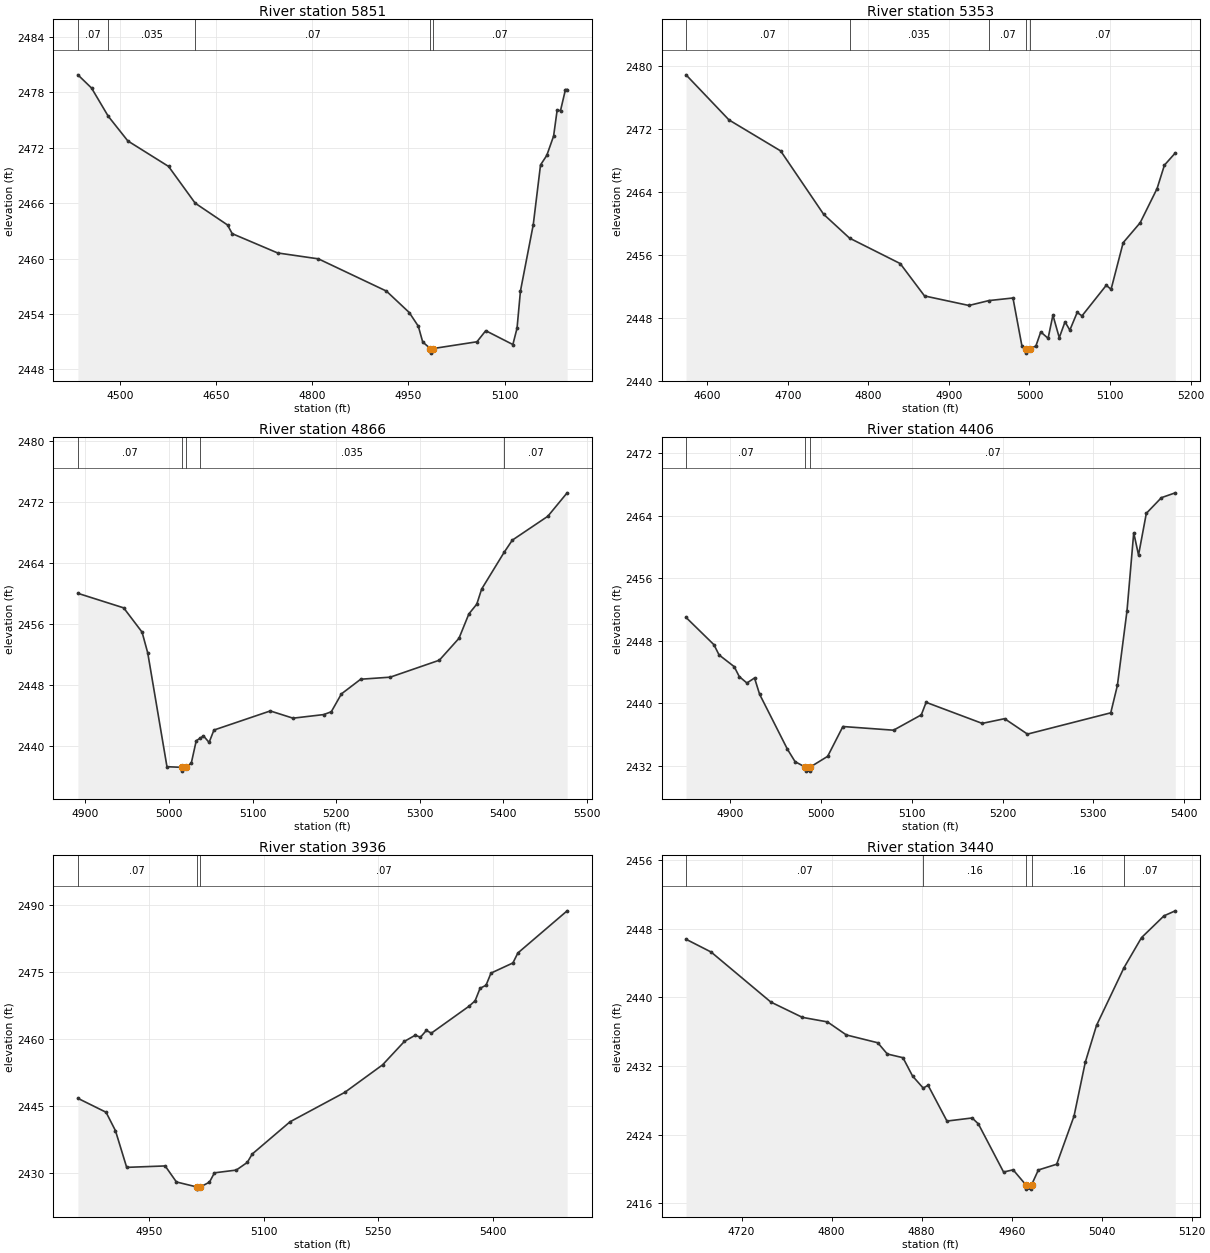
Type RM Length L Ch R = 1,5851,498,498,498
BEGIN DESCRIPTION:
Sweetwater Creek Trib 6 T 11.0
END DESCRIPTION:
XS GIS Cut Line= 3
      1363255.01      6801088.01      1362869.19      6800674.70
      1362805.01      6800488.02
#Sta/Elev= 30
  4434.6 2479.90  4455.9 2478.47  4481.9 2475.42  4512.5 2472.74  4576.0 2469.98
  4617.5 2466.00  4667.9 2463.64  4675.2 2462.70  4746.0 2460.61  4809.6 2459.97
  4915.6 2456.48  4951.2 2454.16  4965.4 2452.67  4972.2 2450.97  4984.0 2450.26
  4984.4 2449.76  4988.8 2450.26  5056.8 2450.99  5070.5 2452.19  5112.8 2450.69
  5119.3 2452.46  5124.6 2456.48  5144.6 2463.68  5155.9 2470.14  5165.7 2471.18
  5176.3 2473.27  5181.8 2476.06  5187.1 2476.03  5194.8 2478.31  5197.4 2478.31
#Mann=5,-1,0
  4434.6    0.07       0  4481.9   0.035       0  4617.5    0.07       0
  4984.0    0.07       0  4988.8    0.07       0
Bank Sta=4984,4988.8
Exp/Cntr=0.3,0.1

Type RM Length L Ch R = 1,5353,487,487,487
BEGIN DESCRIPTION:
Sweetwater Creek Trib 6 T 10.0
END DESCRIPTION:
XS GIS Cut Line= 3
      1363305.00      6801037.99      1363154.99      6800638.85
      1363054.99      6800487.98
#Sta/Elev= 30
  4573.6 2478.86  4627.0 2473.13  4691.1 2469.20  4744.5 2461.15  4776.6 2458.13
  4839.5 2454.90  4869.7 2450.79  4924.8 2449.58  4949.6 2450.20  4979.5 2450.53
  4990.7 2444.39  4995.4 2444.03  4995.7 2443.53  5000.2 2444.03  5008.0 2444.45
  5014.0 2446.22  5023.1 2445.41  5029.1 2448.35  5037.0 2445.49  5044.1 2447.50
  5050.1 2446.45  5059.2 2448.69  5065.2 2448.26  5095.3 2452.14  5101.3 2451.63
  5116.3 2457.55  5137.4 2460.08  5158.4 2464.42  5167.5 2467.39  5181.0 2468.94
#Mann=5,-1,0
  4573.6    0.07       0  4776.6   0.035       0  4949.6    0.07       0
  4995.4    0.07       0  5000.2    0.07       0
Bank Sta=4995.4,5000.2
Exp/Cntr=0.3,0.1

Type RM Length L Ch R = 1,4866,460,460,460
BEGIN DESCRIPTION:
Sweetwater Creek Trib 6 T 9.0
END DESCRIPTION:
XS GIS Cut Line= 3
      1363654.99      6800637.97      1363610.12      6800538.63
      1363204.99      6800287.99
#Sta/Elev= 30
  4891.0 2460.04  4945.8 2458.13  4967.8 2454.94  4974.6 2452.20  4997.6 2437.25
  5015.3 2437.17  5015.7 2436.67  5020.2 2437.17  5026.7 2437.72  5032.6 2440.66
  5037.4 2441.01  5041.3 2441.30  5048.0 2440.44  5053.8 2442.07  5121.2 2444.58
  5148.4 2443.63  5185.0 2444.10  5194.2 2444.47  5206.3 2446.82  5229.4 2448.75
  5264.7 2449.02  5323.5 2451.25  5347.0 2454.13  5358.8 2457.33  5368.3 2458.62
  5374.1 2460.60  5400.9 2465.41  5410.8 2467.03  5453.3 2470.17  5476.4 2473.25
#Mann=5,-1,0
  4891.0    0.07       0  5015.3    0.07       0  5020.2    0.07       0
  5037.4   0.035       0  5400.9    0.07       0
Bank Sta=5015.3,5020.2
Exp/Cntr=0.3,0.1

Type RM Length L Ch R = 1,4406,470,470,470
BEGIN DESCRIPTION:
Sweetwater Creek Trib 6 T 8.0
END DESCRIPTION:
XS GIS Cut Line= 3
      1363955.00      6800338.01      1363888.43      6800204.71
      1363755.01      6799838.03
#Sta/Elev= 30
  4851.0 2450.98  4881.8 2447.49  4887.4 2446.19  4904.1 2444.69  4909.7 2443.42
  4918.1 2442.60  4926.5 2443.24  4932.1 2441.16  4962.8 2434.13  4971.2 2432.55
  4982.6 2431.84  4983.0 2431.34  4987.3 2431.34  4987.6 2431.84  5007.1 2433.23
  5023.9 2437.04  5079.7 2436.57  5110.3 2438.53  5115.6 2440.13  5177.4 2437.44
  5202.1 2438.04  5227.3 2436.07  5319.1 2438.79  5326.4 2442.29  5337.0 2451.83
  5344.4 2461.80  5349.7 2458.95  5358.3 2464.28  5374.9 2466.28  5390.2 2466.90
#Mann=3,-1,0
  4851.0    0.07       0  4982.6    0.07       0  4987.6    0.07       0
Bank Sta=4982.6,4987.6
Exp/Cntr=0.3,0.1

Type RM Length L Ch R = 1,3936,496,496,496
BEGIN DESCRIPTION:
Sweetwater Creek Trib 6 T 7.0
END DESCRIPTION:
XS GIS Cut Line= 3
      1364255.01      6799988.02      1364171.70      6799871.42
      1363855.00      6799488.00
#Sta/Elev= 30
  4856.7 2446.68  4893.6 2443.55  4905.9 2439.41  4920.6 2431.17  4971.0 2431.49
  4985.7 2427.89  5012.1 2426.78  5012.5 2426.28  5017.2 2426.78  5029.0 2427.85
  5035.5 2429.94  5064.1 2430.56  5078.5 2432.28  5085.0 2434.17  5134.5 2441.41
  5206.1 2448.01  5255.6 2454.19  5284.3 2459.48  5298.6 2460.87  5305.1 2460.39
  5313.0 2461.93  5319.5 2461.32  5369.0 2467.39  5376.8 2468.59  5383.3 2471.40
  5391.1 2472.08  5397.6 2474.81  5426.3 2477.09  5432.8 2479.33  5497.3 2488.80
#Mann=3,-1,0
  4856.7    0.07       0  5012.1    0.07       0  5017.2    0.07       0
Bank Sta=5012.1,5017.2
Exp/Cntr=0.3,0.1

Type RM Length L Ch R = 1,3440,496,496,496
BEGIN DESCRIPTION:
Sweetwater Creek Trib 6 T 6.0
END DESCRIPTION:
XS GIS Cut Line= 3
      1364405.01      6799987.98      1364552.43      6799693.41
      1364555.00      6799588.04
#Sta/Elev= 30
  4670.6 2446.75  4692.9 2445.26  4746.0 2439.43  4774.0 2437.65  4796.3 2437.12
  4813.1 2435.60  4841.0 2434.69  4849.5 2433.38  4863.4 2432.95  4871.9 2430.82
  4881.4 2429.41  4885.7 2429.74  4902.5 2425.57  4924.9 2425.93  4930.4 2425.24
  4952.8 2419.63  4961.3 2419.89  4972.6 2418.14  4973.0 2417.64  4977.3 2417.64
  4977.7 2418.14  4983.7 2419.87  5000.0 2420.54  5015.4 2426.14  5025.4 2432.41
  5035.4 2436.71  5059.8 2443.43  5075.4 2446.94  5095.4 2449.48  5105.4 2450.06
#Mann=5,-1,0
  4670.6    0.07       0  4881.4    0.16       0  4972.6    0.07       0
  4977.7    0.16       0  5059.8    0.07       0
Bank Sta=4972.6,4977.7
Exp/Cntr=0.3,0.1

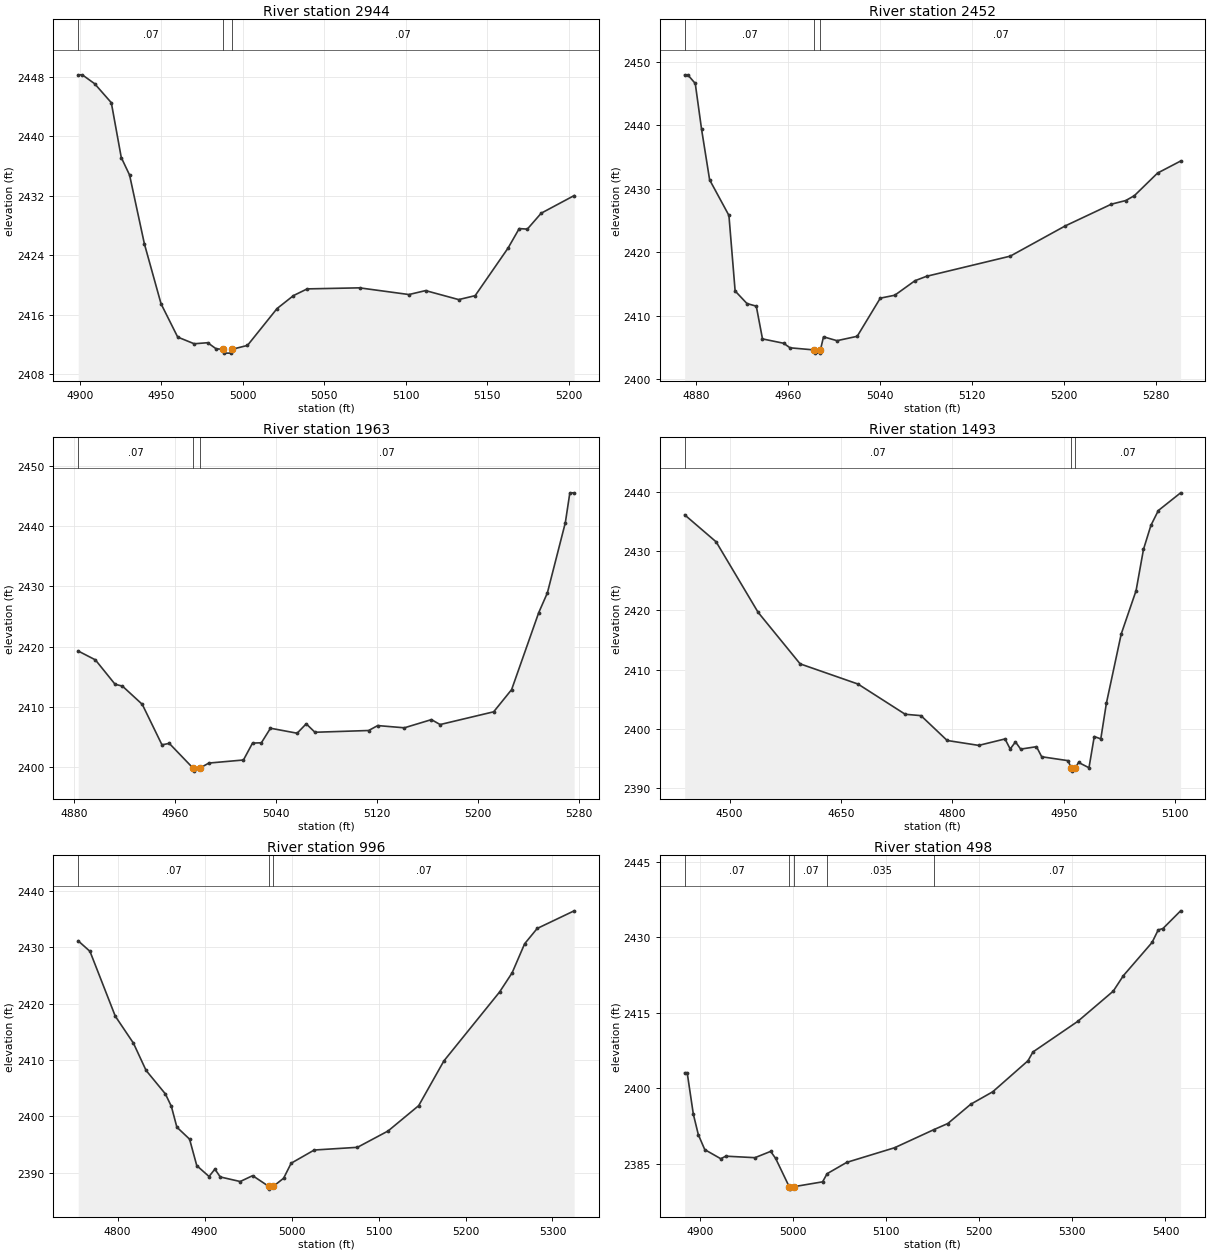
Type RM Length L Ch R = 1,2944,492,492,492
BEGIN DESCRIPTION:
Sweetwater Creek Trib 6 T 5.0
END DESCRIPTION:
XS GIS Cut Line= 3
      1364904.99      6800087.96      1364886.67      6799988.74
      1364855.00      6799788.02
#Sta/Elev= 30
  4899.1 2448.28  4901.6 2448.28  4909.2 2447.08  4919.4 2444.53  4925.5 2437.16
  4930.6 2434.80  4939.7 2425.53  4949.9 2417.48  4960.1 2413.01  4970.2 2412.11
  4978.5 2412.25  4983.6 2411.44  4987.9 2411.35  4988.4 2410.85  4992.8 2410.85
  4993.2 2411.35  5002.9 2411.89  5021.0 2416.84  5031.1 2418.59  5039.5 2419.49
  5071.6 2419.63  5101.9 2418.73  5112.1 2419.26  5132.4 2418.05  5142.5 2418.58
  5162.7 2424.99  5169.5 2427.60  5174.5 2427.53  5183.0 2429.67  5203.2 2432.04
#Mann=3,-1,0
  4899.1    0.07       0  4987.9    0.07       0  4993.2    0.07       0
Bank Sta=4987.9,4993.2
Exp/Cntr=0.3,0.1

Type RM Length L Ch R = 1,2452,489,489,489
BEGIN DESCRIPTION:
Sweetwater Creek Trib 6 T 4.0
END DESCRIPTION:
XS GIS Cut Line= 3
      1365255.01      6799838.02      1365205.03      6799718.01
      1364905.03      6799688.00
#Sta/Elev= 30
  4870.0 2447.92  4872.7 2447.92  4879.2 2446.56  4884.7 2439.34  4891.7 2431.38
  4908.5 2425.77  4913.9 2413.87  4924.2 2411.89  4932.3 2411.48  4937.7 2406.32
  4956.2 2405.63  4961.6 2404.92  4982.8 2404.58  4983.2 2404.08  4987.7 2404.08
  4988.1 2404.58  4990.8 2406.65  5002.5 2406.04  5020.1 2406.73  5040.2 2412.74
  5052.8 2413.20  5070.4 2415.49  5080.4 2416.18  5153.3 2419.36  5201.0 2424.11
  5241.2 2427.54  5253.8 2428.12  5261.3 2428.89  5281.4 2432.44  5301.5 2434.34
#Mann=3,-1,0
  4870.0    0.07       0  4982.8    0.07       0  4988.1    0.07       0
Bank Sta=4982.8,4988.1
Exp/Cntr=0.3,0.1

Type RM Length L Ch R = 1,1963,470,470,470
BEGIN DESCRIPTION:
Sweetwater Creek Trib 6 T 3.0
END DESCRIPTION:
XS GIS Cut Line= 3
      1365304.97      6799287.98      1365204.55      6799228.72
      1365005.03      6799038.03
#Sta/Elev= 30
  4883.4 2419.25  4897.0 2417.78  4912.6 2413.72  4918.4 2413.42  4934.1 2410.39
  4949.7 2403.66  4955.5 2403.90  4974.3 2399.79  4974.7 2399.29  4979.7 2399.79
  4986.8 2400.63  5014.2 2401.14  5021.4 2403.95  5028.4 2404.00  5035.6 2406.42
  5056.7 2405.59  5063.9 2407.15  5070.8 2405.75  5113.3 2406.04  5120.5 2406.86
  5141.6 2406.49  5163.0 2407.85  5169.9 2407.03  5212.3 2409.15  5226.5 2412.84
  5247.9 2425.60  5254.8 2428.91  5269.0 2440.56  5272.6 2445.54  5276.0 2445.54
#Mann=3,-1,0
  4883.4    0.07       0  4974.3    0.07       0  4979.7    0.07       0
Bank Sta=4974.3,4979.7
Exp/Cntr=0.3,0.1

Type RM Length L Ch R = 1,1493,497,497,497
BEGIN DESCRIPTION:
Sweetwater Creek Trib 6 T 2.0
END DESCRIPTION:
XS GIS Cut Line= 3
      1365805.00      6799288.00      1365404.99      6798895.53
      1365405.00      6798788.03
#Sta/Elev= 30
  4439.6 2436.16  4482.0 2431.59  4538.5 2419.68  4595.1 2410.97  4673.0 2407.56
  4736.6 2402.45  4757.8 2402.22  4793.1 2398.02  4835.6 2397.19  4871.0 2398.28
  4878.0 2396.58  4885.1 2397.78  4892.1 2396.56  4913.4 2396.97  4920.4 2395.27
  4955.9 2394.61  4960.2 2393.34  4960.6 2392.84  4965.6 2393.34  4970.0 2394.31
  4984.1 2393.41  4991.2 2398.69  5000.0 2398.29  5007.5 2404.29  5027.5 2416.02
  5047.5 2423.34  5057.5 2430.33  5067.5 2434.38  5077.5 2436.89  5107.5 2439.88
#Mann=3,-1,0
  4439.6    0.07       0  4960.2    0.07       0  4965.6    0.07       0
Bank Sta=4960.2,4965.6
Exp/Cntr=0.3,0.1

Type RM Length L Ch R = 1,996,498,498,498
BEGIN DESCRIPTION:
Sweetwater Creek Trib 6 T 1.0
END DESCRIPTION:
XS GIS Cut Line= 3
      1366004.97      6799087.98      1365809.37      6798940.11
      1365554.99      6798737.99
#Sta/Elev= 30
  4754.8 2431.14  4768.3 2429.28  4797.4 2417.78  4818.3 2412.98  4832.8 2408.15
  4855.0 2403.98  4861.9 2401.76  4868.2 2398.08  4882.8 2395.95  4891.1 2391.25
  4905.2 2389.32  4911.9 2390.63  4918.1 2389.24  4941.0 2388.43  4955.3 2389.47
  4973.7 2387.58  4974.1 2387.08  4979.1 2387.58  4990.9 2389.01  4999.6 2391.68
  5026.1 2394.02  5075.8 2394.50  5111.0 2397.40  5146.2 2401.90  5175.1 2409.82
  5239.2 2422.07  5253.6 2425.47  5268.0 2430.63  5282.4 2433.34  5324.9 2436.47
#Mann=3,-1,0
  4754.8    0.07       0  4973.7    0.07       0  4979.1    0.07       0
Bank Sta=4973.7,4979.1
Exp/Cntr=0.3,0.1

Type RM Length L Ch R = 1,498,393,393,393
BEGIN DESCRIPTION:
Sweetwater Creek Trib 6 T 2110
END DESCRIPTION:
XS GIS Cut Line= 3
      1366155.00      6798737.99      1366111.08      6798629.87
      1365705.04      6798538.01
#Sta/Elev= 30
  4883.3 2403.06  4886.0 2403.06  4892.6 2394.83  4898.0 2390.73  4904.9 2387.78
  4922.1 2385.97  4927.5 2386.48  4958.8 2386.18  4975.7 2387.43  4981.1 2386.02
  4995.6 2380.43  4996.0 2379.93  5001.1 2380.43  5031.5 2381.38  5036.4 2383.00
  5057.5 2385.25  5108.8 2388.15  5151.2 2391.76  5166.1 2392.97  5190.8 2396.81
  5214.4 2399.28  5252.3 2405.45  5257.6 2407.19  5305.9 2413.29  5343.9 2419.28
  5354.8 2422.36  5385.6 2428.95  5392.2 2431.44  5397.3 2431.72  5416.3 2435.24
#Mann=5,-1,0
  4883.3    0.07       0  4995.6    0.07       0  5001.1    0.07       0
  5036.4   0.035       0  5151.2    0.07       0
Bank Sta=4995.6,5001.1
Exp/Cntr=0.3,0.1

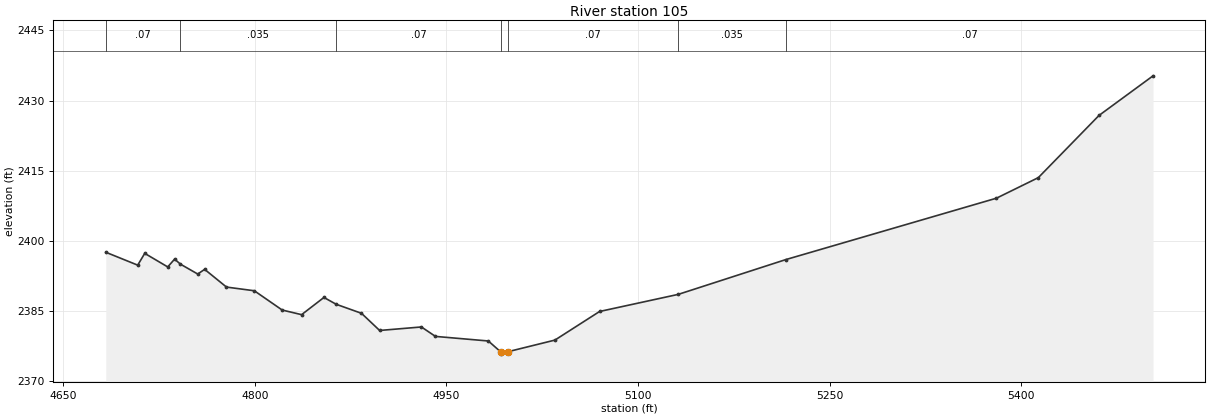
Type RM Length L Ch R = 1,105,0,0,0
BEGIN DESCRIPTION:
Sweetwater Creek Trib 6 T 4510
END DESCRIPTION:
XS GIS Cut Line= 3
      1366330.50      6798564.68      1366204.58      6798274.19
      1365718.21      6798403.63
#Sta/Elev= 30
  4683.4 2397.57  4708.4 2394.81  4713.9 2397.33  4731.9 2394.43  4737.3 2396.10
  4741.8 2395.03  4755.4 2392.91  4760.8 2393.91  4777.9 2390.12  4799.7 2389.33
  4821.5 2385.21  4836.7 2384.22  4854.2 2387.90  4863.8 2386.44  4883.6 2384.51
  4897.8 2380.84  4930.5 2381.59  4941.5 2379.57  4982.9 2378.59  4992.5 2376.28
  4992.9 2375.78  4998.0 2376.28  5035.0 2378.78  5070.0 2384.90  5131.6 2388.56
  5215.8 2396.00  5380.7 2409.13  5413.5 2413.53  5461.0 2426.83  5503.3 2435.30
#Mann=7,-1,0
  4683.4    0.07       0  4741.8   0.035       0  4863.8    0.07       0
  4992.5    0.07       0  4998.0    0.07       0  5131.6   0.035       0
  5215.8    0.07       0
Bank Sta=4992.5,4998
Exp/Cntr=0.3,0.1

Chan Stop Cuts=-1