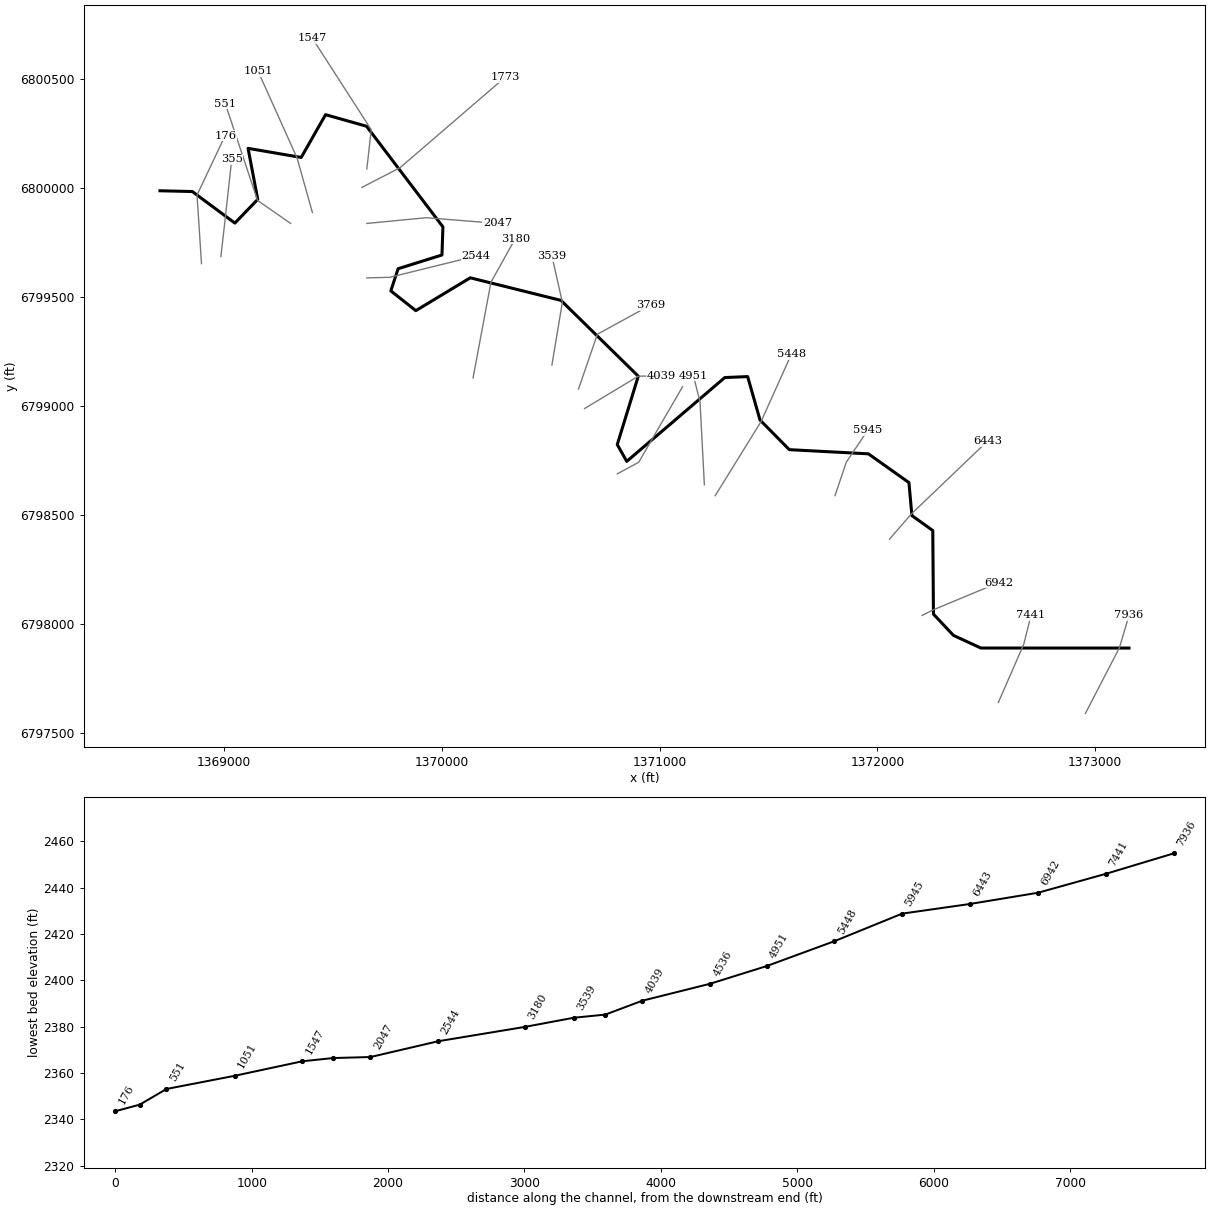
--- Sweetwater Creek Trib 7.prj (project) ---

Proj Title=Sweetwater Creek Trib 7 Base Level Engineering
Current Plan=p01
Default Exp/Contr=0.3,0.1
English Units
Geom File=g01
Flow File=f01
Plan File=p01
Y Axis Title=Elevation
X Axis Title(PF)=Main Channel Distance
X Axis Title(XS)=Station
BEGIN DESCRIPTION:
Sweetwater Creek Trib 7
END DESCRIPTION:
DSS Export Rating Curves= 0
DSS Export Rating Curve Sorted= 0
DSS Export Volume Flow Curves= 0
DXF OffsetX= 0
DXF OffsetY= 0
DXF ScaleX= 1
DXF ScaleY= 10

--- Sweetwater Creek Trib 7.p01 (plan) ---

Plan Title=Multiple Run
Short Identifier=Multiple
Geom File=g01
Flow File=f01
Subcritical Flow
K Sum by GR= 0
Std Step Tol= 0.01
Critical Tol= 0.01
Num of Std Step Trials= 20
Max Error Tol= 0.3
Flow Tol Ratio= 0.001
Split Flow NTrial= 30
Split Flow Tol= 0.02
Split Flow Ratio= 0.02
Log Output Level= 0
Friction Slope Method= 1
Unsteady Friction Slope Method= 2
Unsteady Bridges Friction Slope Method= 1
Parabolic Critical Depth
Global Vel Dist=  1 , 1 , 1
Global Log Level= 0
CheckData=True
Encroach Param= -1, 0, 0, 0
BEGIN DESCRIPTION:
Multiple Run
END DESCRIPTION:

--- Sweetwater Creek Trib 7.f01 (steady flow) ---

Flow Title=Multiple
Number of Profiles=7
Profile Names=10-year,25-year,50-year,1pct_min,100-year,1pct_plu,500-year
River Rch & RM= Sweetwater Creek,Reach-1,7936
     299     427     535     333     665    1328    1043
River Rch & RM= Sweetwater Creek,Reach-1,6443
     521     767     982     625    1248    2489    2038
River Rch & RM= Sweetwater Creek,Reach-1,2544
     505     745     955     608    1214    2422    1988
Boundary for River Rch & Prof#=Sweetwater Creek,Reach-1,1
Up Type=0
Dn Type=3
Dn Slope=0.005
Boundary for River Rch & Prof#=Sweetwater Creek,Reach-1,2
Up Type=0
Dn Type=3
Dn Slope=0.005
Boundary for River Rch & Prof#=Sweetwater Creek,Reach-1,3
Up Type=0
Dn Type=3
Dn Slope=0.005
Boundary for River Rch & Prof#=Sweetwater Creek,Reach-1,4
Up Type=0
Dn Type=3
Dn Slope=0.005
Boundary for River Rch & Prof#=Sweetwater Creek,Reach-1,5
Up Type=0
Dn Type=3
Dn Slope=0.005
Boundary for River Rch & Prof#=Sweetwater Creek,Reach-1,6
Up Type=0
Dn Type=3
Dn Slope=0.005
Boundary for River Rch & Prof#=Sweetwater Creek,Reach-1,7
Up Type=0
Dn Type=3
Dn Slope=0.005

--- Sweetwater Creek Trib 7.g01 (geometry) ---

Geom Title=Existing Conditions
Program Version=4.10

River Reach=Sweetwater Creek,Reach-1
Reach XY= 30
        1373155.        6797888.      1372475.03      6797888.06
      1372348.92      6797946.13      1372257.05      6798043.84
      1372253.99      6798427.71      1372158.11      6798496.32
      1372144.53      6798647.82      1371958.31      6798779.93
      1371594.94       6798799.1      1371460.47      6798935.55
      1371403.75      6799134.64      1371298.83      6799130.24
      1370848.57      6798745.34      1370805.01      6798822.51
      1370901.54       6799136.5      1370546.56      6799484.59
      1370129.95      6799588.35      1369879.96      6799437.49
      1369765.16      6799528.31      1369798.56      6799629.98
      1369999.98      6799693.09      1370004.36      6799822.14
       1369653.5      6800284.39      1369465.45      6800337.47
      1369353.61      6800141.03       1369109.6      6800182.84
      1369153.97      6799948.43      1369048.96      6799839.57
      1368853.55       6799984.5        1368705.        6799988.

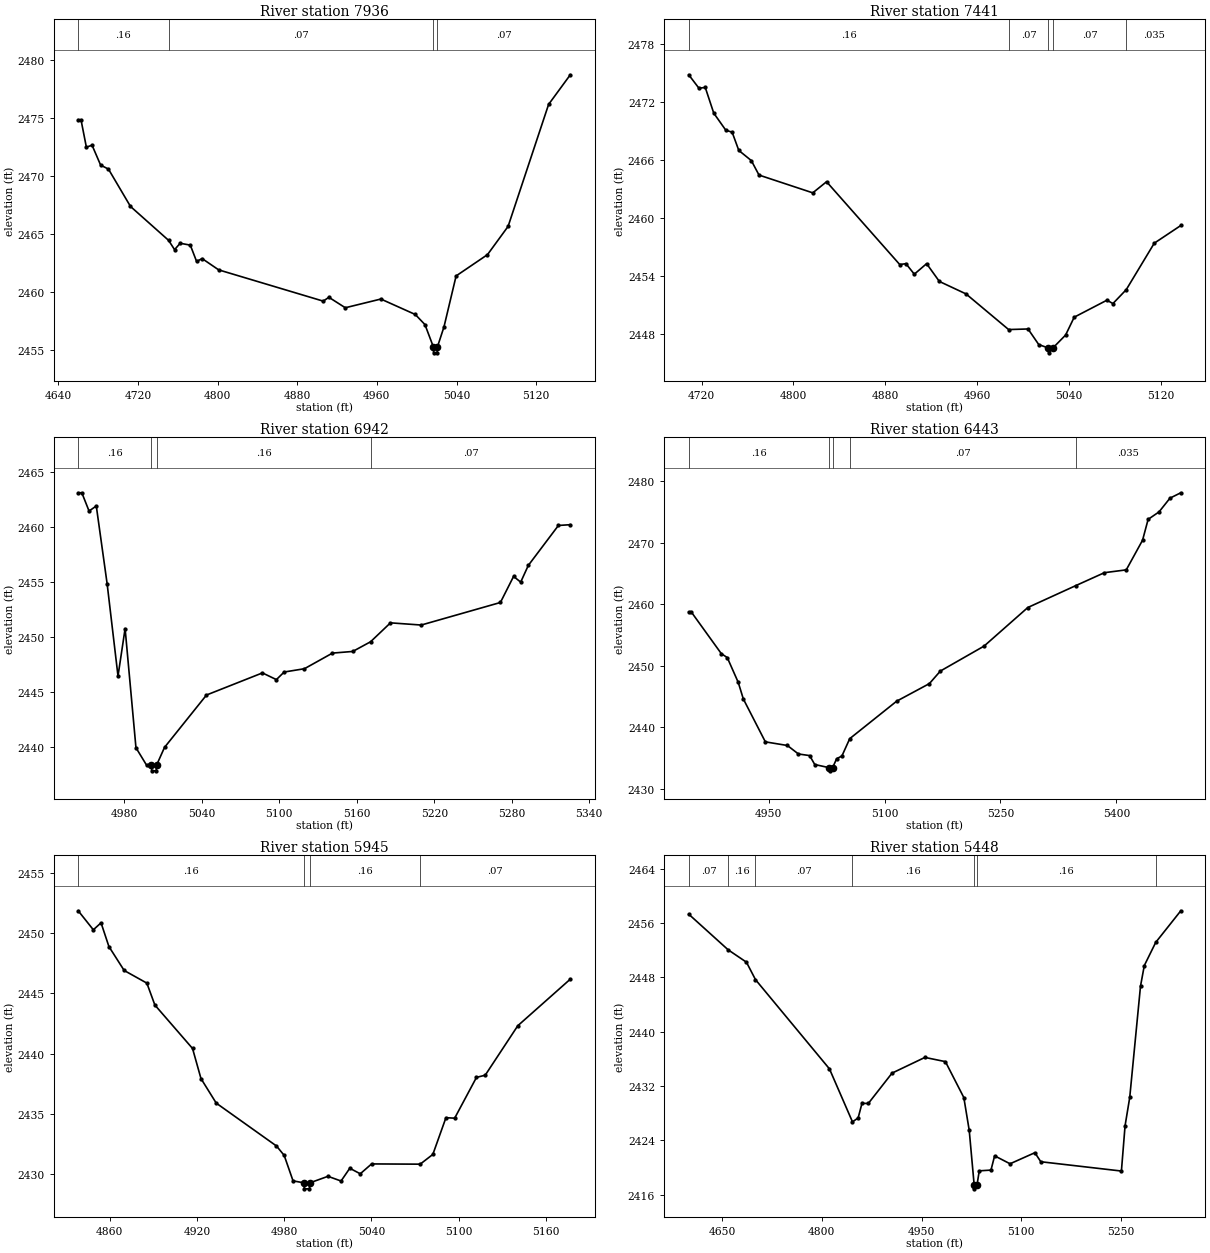
Type RM Length L Ch R = 1 ,7936    ,495,495,495
BEGIN DESCRIPTION:
Sweetwater Creek Trib 7 14.0
END DESCRIPTION:
XS GIS Cut Line= 3
      1372955.01      6797588.03      1373111.27      6797889.99
      1373154.99      6798037.97
#Sta/Elev= 30
    4660 2474.84  4662.8 2474.84  4668.2 2472.48  4673.9 2472.65  4682.5 2470.94
  4690.4 2470.59  4712.5 2467.38  4750.8 2464.46  4756.8 2463.66  4762.4 2464.21
  4772.6 2464.05  4778.9 2462.65  4784.5 2462.89  4801.1 2461.92  4906.1 2459.23
  4911.8 2459.56  4928.3 2458.66    4964 2459.41  4998.6 2458.08  5008.3 2457.21
  5016.8 2455.28    5017 2454.78  5020.5 2454.78  5020.8 2455.28  5027.4 2457.01
  5039.6  2461.4  5071.1 2463.23  5091.8 2465.66  5132.5 2476.16  5154.3 2478.71
#Mann= 4 ,-1 , 0
    4660     .16       0  4750.8     .07       0  5016.8     .07       0
  5020.8     .07       0
Bank Sta=5016.8,5020.8
XS Rating Curve= 0 ,0
Exp/Cntr=0.3,0.1

Type RM Length L Ch R = 1 ,7441    ,499,499,499
BEGIN DESCRIPTION:
Sweetwater Creek Trib 7 13.0
END DESCRIPTION:
XS GIS Cut Line= 3
      1372555.02      6797638.04      1372671.57      6797904.89
      1372704.99      6798037.96
#Sta/Elev= 30
  4708.8 2474.78  4717.7 2473.39  4723.2 2473.47  4730.6 2470.81  4741.1 2469.04
  4746.6 2468.84  4752.4 2466.95  4763.3  2465.9    4770  2464.4  4816.8 2462.56
  4828.8 2463.71  4892.5 2455.14  4897.9 2455.23  4905.2 2454.14  4915.9 2455.23
    4927 2453.39  4950.2  2452.1  4987.3 2448.41  5004.2 2448.47  5013.5 2446.86
  5021.8  2446.5  5022.1    2446  5025.8  2446.5  5036.9 2447.84  5044.4 2449.69
  5072.9 2451.45  5078.1  2451.1  5089.7 2452.54  5114.1 2457.35  5137.2 2459.18
#Mann= 5 ,-1 , 0
  4708.8     .16       0  4987.3     .07       0  5021.8     .07       0
  5025.8     .07       0  5089.7    .035       0
Bank Sta=5021.8,5025.8
XS Rating Curve= 0 ,0
Exp/Cntr=0.3,0.1

Type RM Length L Ch R = 1 ,6942    ,499,499,499
BEGIN DESCRIPTION:
Sweetwater Creek Trib 7 12.0
END DESCRIPTION:
XS GIS Cut Line= 3
      1372204.98      6798037.99       1372254.7      6798062.87
      1372554.98      6798187.99
#Sta/Elev= 30
  4944.4 2463.07  4947.2 2463.07  4952.8 2461.41  4958.4 2461.87  4966.8 2454.79
  4975.2 2446.41  4980.7 2450.73  4989.1  2439.9  4997.4  2438.3    5001  2438.3
  5001.3  2437.8  5004.8  2437.8    5005  2438.3  5011.2 2439.93  5043.7 2444.69
    5087  2446.7  5097.8 2446.09  5103.8 2446.78  5119.5 2447.08  5141.2  2448.5
  5156.9 2448.65  5170.7 2449.53  5186.1 2451.25  5209.9 2451.05  5271.2  2453.1
  5281.4 2455.47  5286.9 2454.95  5292.8 2456.47  5316.1  2460.1  5325.3 2460.17
#Mann= 4 ,-1 , 0
  4944.4     .16       0    5001     .07       0    5005     .16       0
  5170.7     .07       0
Bank Sta=5001,5005
XS Rating Curve= 0 ,0
Exp/Cntr=0.3,0.1

Type RM Length L Ch R = 1 ,6443    ,498,498,498
BEGIN DESCRIPTION:
Sweetwater Creek Trib 7 11.0
END DESCRIPTION:
XS GIS Cut Line= 3
        1372055.      6798387.99      1372155.69      6798503.85
        1372505.        6798838.
#Sta/Elev= 30
  4846.5 2458.78  4849.8 2458.78  4888.7    2452  4896.4 2451.36  4910.6 2447.33
  4917.2 2444.63  4945.7 2437.66  4974.2 2437.07  4988.5 2435.69    5003 2435.43
  5009.6 2433.98  5028.7 2433.45  5028.9 2432.95  5032.7 2433.45  5037.9 2434.91
  5044.8 2435.37  5054.9 2438.18  5115.6 2444.27    5158 2447.13  5172.2 2449.17
  5228.8 2453.23  5285.4  2459.5  5347.3 2463.05  5384.5 2465.16  5412.8 2465.62
  5433.9 2470.44  5441.1 2473.83  5455.2 2475.04  5469.4 2477.28  5483.4 2478.15
#Mann= 5 ,-1 , 0
  4846.5     .16       0  5028.7     .07       0  5032.7     .16       0
  5054.9     .07       0  5347.3    .035       0
Bank Sta=5028.7,5032.7
XS Rating Curve= 0 ,0
Exp/Cntr=0.3,0.1

Type RM Length L Ch R = 1 ,5945    ,497,497,497
BEGIN DESCRIPTION:
Sweetwater Creek Trib 7 10.0
END DESCRIPTION:
XS GIS Cut Line= 3
      1371805.01      6798588.04      1371856.65      6798741.17
      1371954.99      6798887.98
#Sta/Elev= 30
  4838.4 2451.87  4848.8 2450.29  4854.1 2450.87  4859.5  2448.9    4870 2446.91
  4885.6 2445.86  4891.1 2444.04    4917 2440.43  4922.8 2437.93  4933.3 2435.89
  4974.7 2432.33    4980 2431.55  4986.1 2429.43  4993.6 2429.27  4993.9 2428.77
  4997.4 2428.77  4997.7 2429.27  5010.1 2429.81  5019.1 2429.42  5025.1 2430.48
  5032.3 2430.02  5040.1 2430.84  5073.5 2430.82  5082.2 2431.63  5091.2 2434.68
  5097.2 2434.64  5112.2 2438.03  5118.2 2438.21  5140.6 2442.32  5176.7 2446.19
#Mann= 4 ,-1 , 0
  4838.4     .16       0  4993.6     .07       0  4997.7     .16       0
  5073.5     .07       0
Bank Sta=4993.6,4997.7
XS Rating Curve= 0 ,0
Exp/Cntr=0.3,0.1

Type RM Length L Ch R = 1 ,5448    ,497,497,497
BEGIN DESCRIPTION:
Sweetwater Creek Trib 7 9.0
END DESCRIPTION:
XS GIS Cut Line= 3
      1371255.02      6798588.04      1371465.48       6798928.2
      1371605.01      6799238.03
#Sta/Elev= 30
    4600  2457.3  4659.3 2452.05  4686.8 2450.23  4700.4 2447.66  4811.6 2434.52
  4846.2 2426.72  4854.7  2427.3  4860.5 2429.45    4870 2429.43  4905.7  2433.9
  4955.1 2436.21  4985.9 2435.59  5013.6  2430.3  5021.7 2425.48  5029.2 2417.36
  5029.5 2416.86  5033.3 2417.36  5036.8 2419.51  5054.4 2419.62  5059.9 2421.72
  5083.1 2420.55  5120.4 2422.18  5129.3 2420.85  5250.5 2419.48    5256 2426.15
    5263 2430.31  5279.2  2446.7  5284.9 2449.73  5302.1 2453.15  5339.8  2457.8
#Mann= 7 ,-1 , 0
    4600     .07       0  4659.3     .16       0  4700.4     .07       0
  4846.2     .16       0  5029.2     .07       0  5033.3     .16       0
  5302.1    .035       0
Bank Sta=5029.2,5033.3
XS Rating Curve= 0 ,0
Exp/Cntr=0.3,0.1

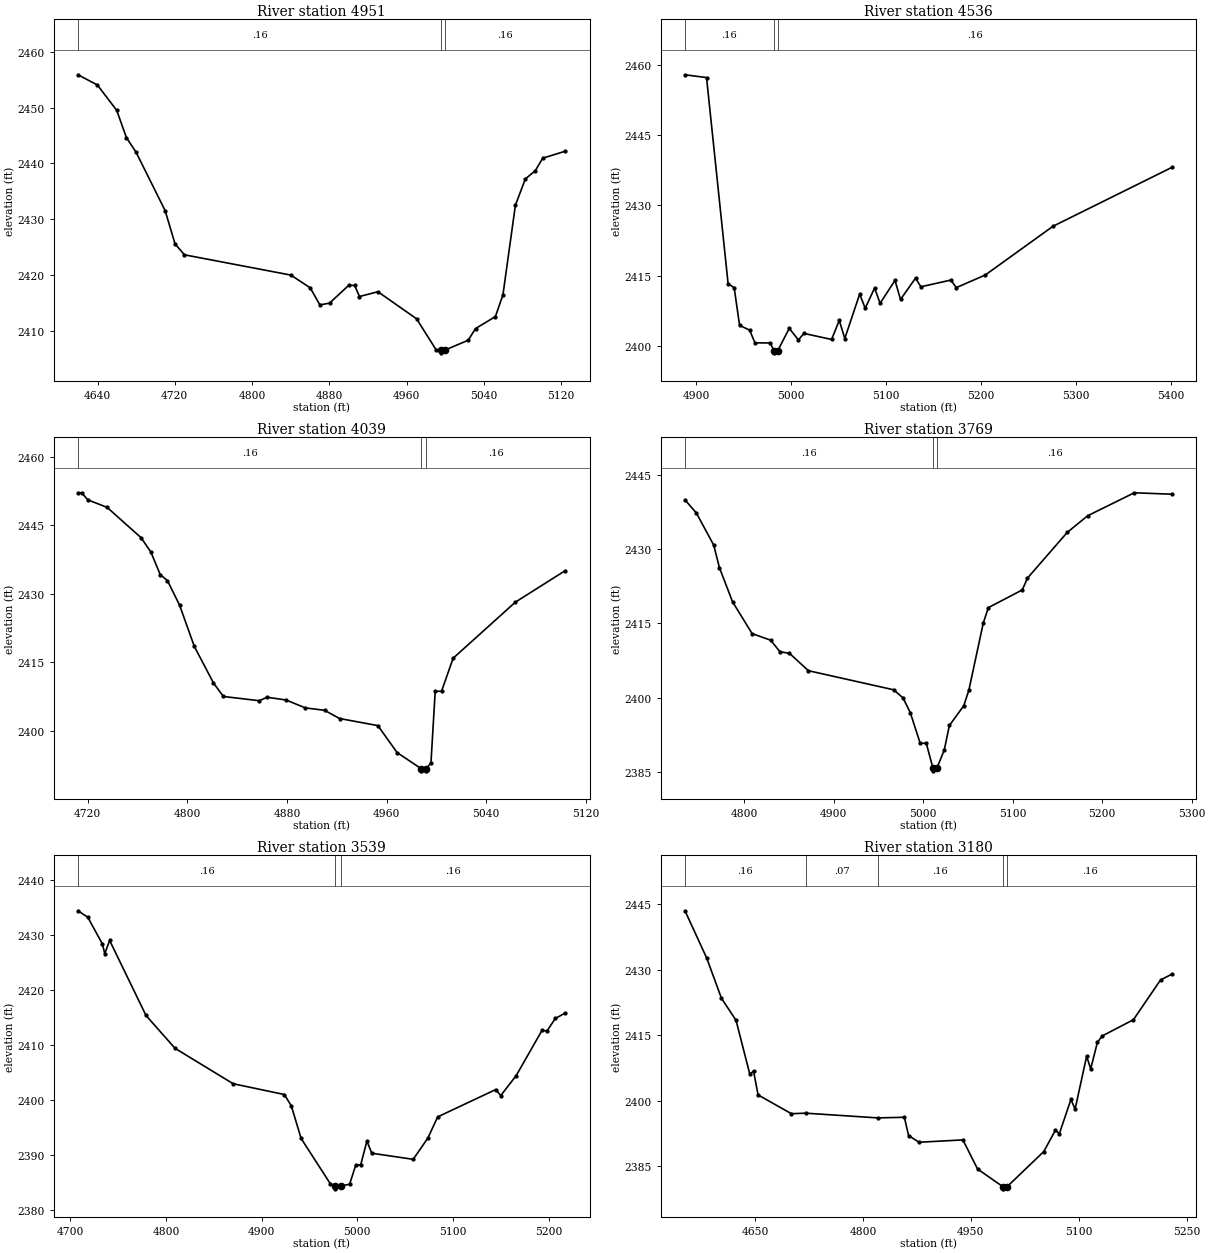
Type RM Length L Ch R = 1 ,4951    ,415,415,415
BEGIN DESCRIPTION:
Sweetwater Creek Trib 7 8.0
END DESCRIPTION:
XS GIS Cut Line= 3
        1371205.      6798638.04      1371185.15      6799017.62
        1371155.        6799138.
#Sta/Elev= 30
  4619.9 2455.86  4639.9 2454.03  4659.9 2449.49  4669.9 2444.63  4679.9 2442.01
    4710 2431.56  4720.3  2425.6    4730 2423.65  4840.2 2420.02  4860.2 2417.74
  4870.2 2414.69  4880.2    2415  4900.2 2418.21  4906.2 2418.16  4911.2 2416.19
  4930.3 2417.04  4970.3  2412.2  4990.4 2406.68  4995.6 2406.61  4995.9 2406.11
  4999.7 2406.61  5023.7 2408.36  5031.3 2410.45  5051.9  2412.6  5059.7 2416.49
  5072.6 2432.52  5082.9 2437.23  5093.2  2438.7  5100.9 2440.94  5124.1 2442.18
#Mann= 3 ,-1 , 0
  4619.9     .16       0  4995.6     .07       0  4999.7     .16       0
Bank Sta=4995.6,4999.7
XS Rating Curve= 0 ,0
Exp/Cntr=0.3,0.1

Type RM Length L Ch R = 1 ,4536    ,497,497,497
BEGIN DESCRIPTION:
Sweetwater Creek Trib 7 7.0
END DESCRIPTION:
XS GIS Cut Line= 3
      1370805.03      6798688.02      1370903.32      6798741.08
      1371105.01      6799088.02
#Sta/Elev= 30
  4888.3 2457.94    4911 2457.34  4933.7 2413.28  4940.1  2412.4  4945.8 2404.35
  4956.4 2403.32    4962 2400.61  4978.2 2400.58  4981.8 2398.97  4982.1 2398.47
  4986.1 2398.97  4998.1  2403.7  5007.8 2401.23  5013.5 2402.63  5042.7 2401.33
  5050.8 2405.41  5056.6 2401.53  5072.3 2411.04  5078.1    2408    5088 2412.33
  5093.8 2409.06  5109.5 2413.96  5115.3 2409.89  5131.1 2414.44  5136.8  2412.6
  5168.3 2414.03  5174.1 2412.42  5204.6 2415.12  5275.9 2425.54  5401.3 2438.15
#Mann= 3 ,-1 , 0
  4888.3     .16       0  4981.8     .07       0  4986.1     .16       0
Bank Sta=4981.8,4986.1
XS Rating Curve= 0 ,0
Exp/Cntr=0.3,0.1

Type RM Length L Ch R = 1 ,4039    ,270,270,270
BEGIN DESCRIPTION:
Sweetwater Creek Trib 7 6.0
END DESCRIPTION:
XS GIS Cut Line= 3
      1370655.01      6798988.01      1370901.54       6799136.5
      1371005.03        6799138.
#Sta/Elev= 30
  4712.2 2452.17  4715.1 2452.17    4720 2450.62  4735.5 2448.97  4762.7 2442.34
  4770.6 2439.21  4778.2 2434.21    4784 2432.89  4793.7 2427.53  4805.6 2418.45
  4820.9 2410.47  4828.9 2407.47  4857.8 2406.54    4864  2407.3  4879.2  2406.7
  4894.7 2404.97  4910.2 2404.43  4922.3 2402.63    4953 2401.08  4968.5 2395.16
  4987.7 2391.65    4988 2391.15  4991.7 2391.15    4992 2391.65  4995.7 2392.92
  4999.1 2408.61  5004.2 2408.61  5013.5 2415.86  5063.5 2428.17  5103.5 2435.07
#Mann= 3 ,-1 , 0
  4712.2     .16       0  4987.7     .07       0    4992     .16       0
Bank Sta=4987.7,4992
XS Rating Curve= 0 ,0
Exp/Cntr=0.3,0.1

Type RM Length L Ch R = 1 ,3769    ,230,230,230
BEGIN DESCRIPTION:
Sweetwater Creek Trib 7 4161
END DESCRIPTION:
XS GIS Cut Line= 3
      1370627.08      6799077.67      1370713.79      6799329.24
      1370957.68      6799462.88
#Sta/Elev= 30
  4733.9 2439.96  4746.5 2437.34    4766 2430.82  4772.4 2426.25  4787.1 2419.33
  4808.9 2412.92  4829.5  2411.6  4840.1 2409.24  4850.6 2408.94  4871.8 2405.42
    4967 2401.56  4977.5 2399.93  4985.6 2396.94  4996.7 2390.75  5003.5 2390.75
    5011 2385.67  5011.3 2385.17  5015.3 2385.67  5023.6  2389.4  5029.3 2394.34
  5045.4 2398.34  5051.1  2401.5  5067.2 2415.08  5072.9 2418.18  5110.8 2421.76
  5116.5 2424.13    5161 2433.39  5183.8 2436.75  5235.9  2441.4  5278.1 2441.11
#Mann= 3 ,-1 , 0
  4733.9     .16       0    5011     .07       0  5015.3     .16       0
Bank Sta=5011,5015.3
XS Rating Curve= 0 ,0
Exp/Cntr=0.3,0.1

Type RM Length L Ch R = 1 ,3539    ,359,359,359
BEGIN DESCRIPTION:
Sweetwater Creek Trib 7 5.0
END DESCRIPTION:
XS GIS Cut Line= 3
        1370505.      6799187.98      1370552.86      6799475.92
        1370505.      6799687.99
#Sta/Elev= 30
  4708.1 2434.42  4718.3 2433.23  4733.5 2428.39    4736 2426.62  4741.1 2429.02
  4779.1 2415.38  4809.5 2409.39  4870.3 2402.95  4923.8 2400.99  4931.1 2398.91
  4941.3    2393  4971.7  2384.8  4976.7 2384.33  4977.2 2383.83  4982.7 2384.33
    4992 2384.67  4998.5 2388.17  5003.6 2388.17  5010.1 2392.52  5015.2 2390.31
  5058.5  2389.2  5073.9 2393.08  5084.1 2396.92  5144.9  2401.9    5150 2400.79
  5166.2 2404.43  5193.2 2412.66  5198.4 2412.56  5207.2 2414.84  5217.4  2415.8
#Mann= 3 ,-1 , 0
  4708.1     .16       0  4976.7     .07       0  4982.7     .16       0
Bank Sta=4976.7,4982.7
XS Rating Curve= 0 ,0
Exp/Cntr=0.3,0.1

Type RM Length L Ch R = 1 ,3180    ,636,636,636
BEGIN DESCRIPTION:
Sweetwater Creek Trib 7 4160
END DESCRIPTION:
XS GIS Cut Line= 3
      1370142.69      6799128.17      1370224.94      6799567.94
      1370336.83      6799768.66
#Sta/Elev= 30
  4552.6 2443.56  4582.9 2432.69  4603.3 2423.52  4623.6 2418.46  4642.8 2406.09
  4647.9 2406.86  4654.2 2401.39  4700.5 2397.08  4720.5  2397.2  4820.6 2396.12
  4857.6 2396.26  4863.5 2392.08    4878 2390.54    4939 2391.08  4959.4 2384.41
  4994.5 2380.37    4995 2379.87  5000.5 2380.37  5051.5 2388.42  5067.5 2393.26
  5073.2 2392.54  5089.2 2400.34    5095 2398.13    5111 2410.22  5116.7 2407.36
    5126 2413.44  5132.7 2414.89  5176.1 2418.61  5213.8 2427.72  5229.8 2429.06
#Mann= 5 ,-1 , 0
  4552.6     .16       0  4720.5     .07       0  4820.6     .16       0
  4994.5     .07       0  5000.5     .16       0
Bank Sta=4994.5,5000.5
XS Rating Curve= 0 ,0
Exp/Cntr=0.3,0.1

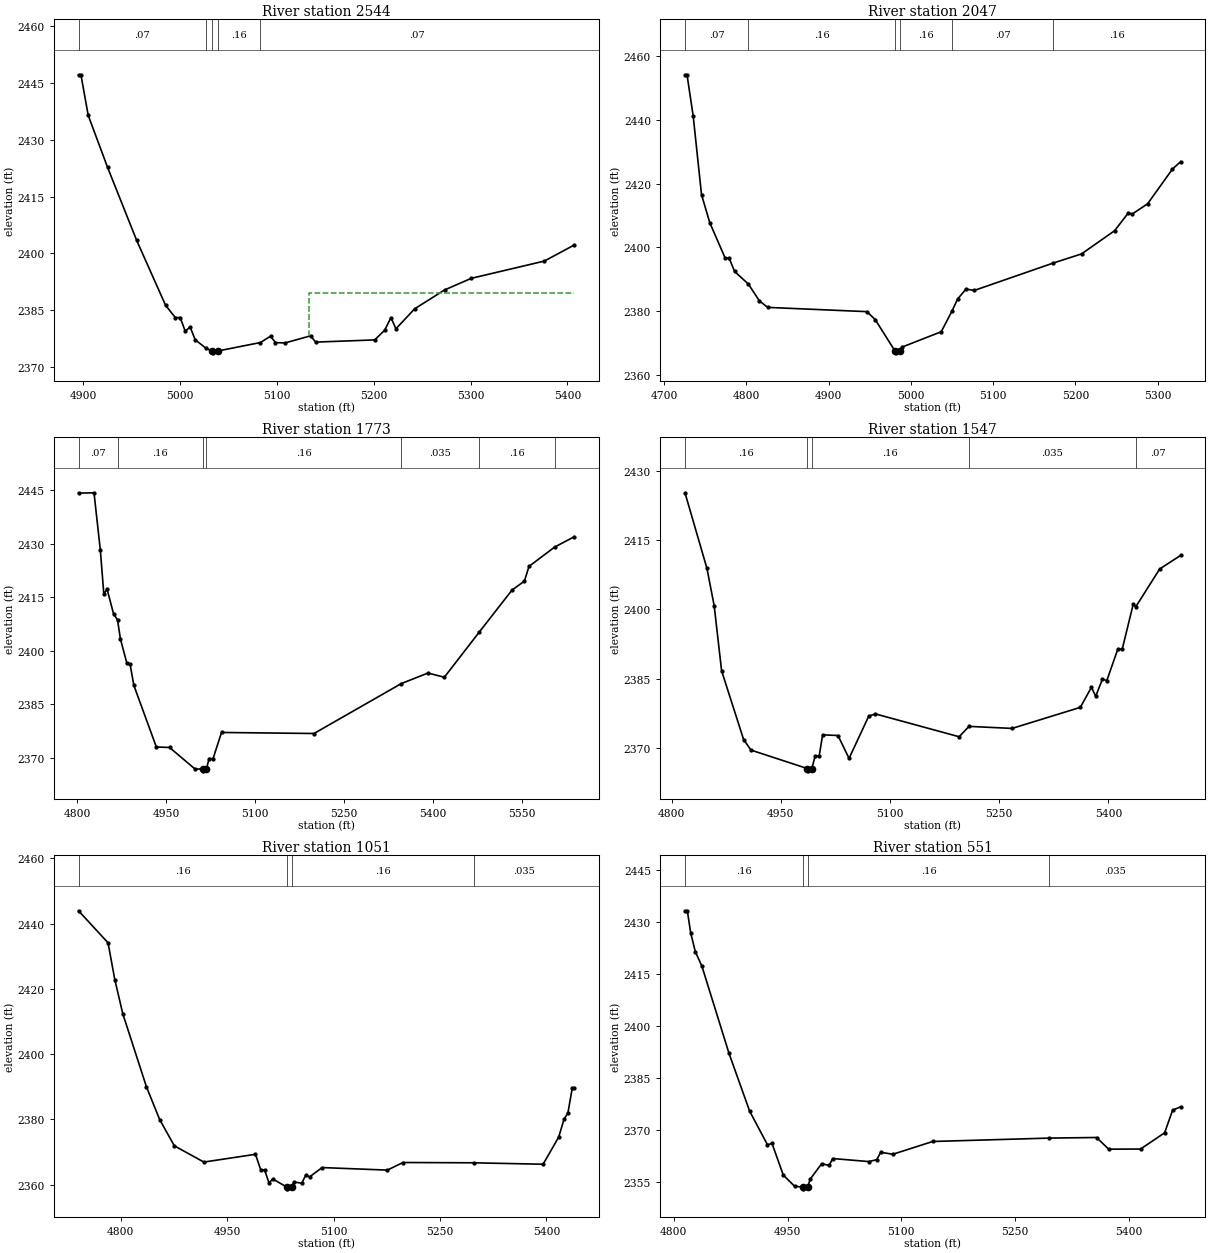
Type RM Length L Ch R = 1 ,2544    ,497,497,497
BEGIN DESCRIPTION:
Sweetwater Creek Trib 7 4.0
END DESCRIPTION:
XS GIS Cut Line= 3
      1369654.99        6799588.      1369759.96      6799590.54
      1370155.01        6799688.
#Sta/Elev= 30
    4895  2447.2  4897.5  2447.2    4905 2436.48    4925 2422.72    4955 2403.44
    4985  2386.2    4995 2382.99    5000 2382.99  5005.2 2379.41  5010.3 2380.49
  5015.5 2377.13  5026.9 2374.84  5033.1 2374.17  5033.6 2373.67  5039.1 2374.17
  5082.9  2376.4  5093.3 2378.08  5098.4 2376.38  5108.2 2376.28  5134.7 2378.17
  5139.9 2376.51  5200.9 2377.09  5211.2 2379.65  5217.7    2383  5222.8 2380.02
  5242.1  2385.3    5273 2390.29  5300.6 2393.37    5376 2397.93  5406.9 2402.17
#Mann= 5 ,-1 , 0
    4895     .07       0  5026.9     .16       0  5033.1     .07       0
  5039.1     .16       0  5082.9     .07       0
#XS Ineff= 2 , 0
                          5133.3         2389.42
Permanent Ineff=
       F       F
Bank Sta=5033.1,5039.1
XS Rating Curve= 0 ,0
Exp/Cntr=0.3,0.1

Type RM Length L Ch R = 1 ,2047    ,274,274,274
BEGIN DESCRIPTION:
Sweetwater Creek Trib 7 3.0
END DESCRIPTION:
XS GIS Cut Line= 3
      1369655.01        6799838.      1369928.24      6799864.32
      1370254.99        6799838.
#Sta/Elev= 30
  4725.5  2454.2    4728  2454.2  4735.5 2441.17  4745.6 2416.56  4755.6 2407.75
  4774.2  2396.7  4779.2 2396.57  4785.8 2392.42  4802.6 2388.44  4815.9 2383.19
    4826 2381.13  4946.5 2379.79  4956.6 2377.32  4980.9 2367.35  4981.4 2366.85
    4987 2367.35    4989 2368.63  5036.9 2373.48    5050    2380  5056.9 2383.79
    5067 2386.89    5077 2386.45  5172.9 2395.05  5207.4 2397.93  5247.6 2405.22
  5264.1 2410.76  5269.1 2410.48  5287.7 2413.68  5317.8 2424.56  5327.8 2426.91
#Mann= 6 ,-1 , 0
  4725.5     .07       0  4802.6     .16       0  4980.9     .07       0
    4987     .16       0    5050     .07       0  5172.9     .16       0
Bank Sta=4980.9,4987
XS Rating Curve= 0 ,0
Exp/Cntr=0.3,0.1

Type RM Length L Ch R = 1 ,1773    ,226,226,226
BEGIN DESCRIPTION:
Sweetwater Creek Trib 7 4159
END DESCRIPTION:
XS GIS Cut Line= 3
      1369632.35      6800003.34      1369807.74      6800094.13
      1370290.85      6800509.92
#Sta/Elev= 30
  4802.5 2444.12  4828.6 2444.23  4839.3 2428.15  4845.1 2415.94  4850.7 2417.21
  4861.6  2410.3  4868.2 2408.68  4873.1 2403.31  4883.7 2396.69  4889.4 2396.26
  4895.6 2390.38  4933.6 2373.08  4955.8 2372.95  4998.8 2366.92  5011.8 2366.91
  5012.3 2366.41  5017.9 2366.91  5022.5 2369.85  5029.1 2369.81  5043.4 2377.15
  5199.2 2376.86  5346.2 2390.83  5391.2 2393.78  5418.7  2392.6    5477 2405.13
  5532.8 2417.02  5553.6  2419.5  5561.3 2423.63  5604.4 2429.02  5637.4 2431.92
#Mann= 7 ,-1 , 0
  4802.5     .07       0  4868.2     .16       0  5011.8     .07       0
  5017.9     .16       0  5346.2    .035       0    5477     .16       0
  5604.4     .07       0
Bank Sta=5011.8,5017.9
XS Rating Curve= 0 ,0
Exp/Cntr=0.3,0.1

Type RM Length L Ch R = 1 ,1547    ,496,496,496
BEGIN DESCRIPTION:
Sweetwater Creek Trib 7 2.0
END DESCRIPTION:
XS GIS Cut Line= 3
        1369655.        6800088.      1369675.16      6800268.37
      1369404.98      6800688.03
#Sta/Elev= 30
  4818.5 2425.31  4848.7 2408.89  4858.6 2400.81  4868.8  2386.7    4899  2371.8
  4909.1 2369.51  4986.5 2365.51    4987 2365.01  4992.7 2365.51  4997.3 2368.24
  5002.8 2368.24  5007.5 2372.82  5028.6 2372.67  5043.8 2367.71  5070.9 2376.89
  5080.1 2377.35    5195  2372.4  5208.5 2374.65  5267.7 2374.21  5361.4 2378.78
  5376.6 2383.13  5382.5 2381.18  5391.8 2384.93  5397.7 2384.56  5412.9 2391.43
  5418.9 2391.38    5434 2401.15  5437.6 2400.61  5470.3 2408.78  5499.1 2411.73
#Mann= 5 ,-1 , 0
  4818.5     .16       0  4986.5     .07       0  4992.7     .16       0
  5208.5    .035       0  5437.6     .07       0
Bank Sta=4986.5,4992.7
XS Rating Curve= 0 ,0
Exp/Cntr=0.3,0.1

Type RM Length L Ch R = 1 ,1051    ,500,500,500
BEGIN DESCRIPTION:
Sweetwater Creek Trib 7 1.0
END DESCRIPTION:
XS GIS Cut Line= 3
        1369405.      6799887.99      1369334.98      6800137.55
      1369155.01      6800537.97
#Sta/Elev= 30
  4740.8 2443.96  4782.4 2434.14  4791.9 2422.89  4803.1 2412.46  4836.4 2390.07
  4855.1 2379.98  4875.8 2371.92  4917.4 2366.94  4990.1 2369.33  4997.6  2364.5
    5003  2364.5  5009.1 2360.56  5014.5 2361.75  5034.6 2359.24  5035.1 2358.74
  5040.9 2359.24  5044.3 2360.84  5055.3 2360.47  5060.9 2362.94  5066.3  2362.4
    5084 2365.26  5175.9 2364.48  5197.8 2366.81  5297.7 2366.72  5395.2 2366.28
  5417.1 2374.55  5424.7 2380.03  5430.2 2382.03  5436.3 2389.57    5439 2389.57
#Mann= 4 ,-1 , 0
  4740.8     .16       0  5034.6     .07       0  5040.9     .16       0
  5297.7    .035       0
Bank Sta=5034.6,5040.9
XS Rating Curve= 0 ,0
Exp/Cntr=0.3,0.1

Type RM Length L Ch R = 1 ,551     ,196,196,196
BEGIN DESCRIPTION:
Sweetwater Creek Trib 7 2641
END DESCRIPTION:
XS GIS Cut Line= 3
      1369305.04      6799837.98      1369152.96      6799943.85
      1369004.98      6800388.05
#Sta/Elev= 30
  4814.7 2433.32  4817.8 2433.32  4822.2 2426.98  4828.3 2421.54    4837 2417.34
  4872.8 2392.12    4900 2375.46  4923.4  2365.8  4929.5 2366.14  4944.3 2357.03
  4959.2  2353.8    4970 2353.55  4970.5 2353.05  4976.3 2353.55  4980.1 2355.94
    4995 2360.33  5004.7  2359.8  5009.5  2361.8  5057.1 2360.92  5067.5 2361.47
  5072.8 2363.61  5088.7 2363.03  5141.4 2366.72  5295.2  2367.7  5357.4 2367.87
  5373.3  2364.5  5415.4 2364.54  5447.1 2369.23  5457.6 2375.75  5468.2 2376.73
#Mann= 4 ,-1 , 0
  4814.7     .16       0    4970     .07       0  4976.3     .16       0
  5295.2    .035       0
Bank Sta=4970,4976.3
XS Rating Curve= 0 ,0
Exp/Cntr=0.3,0.1

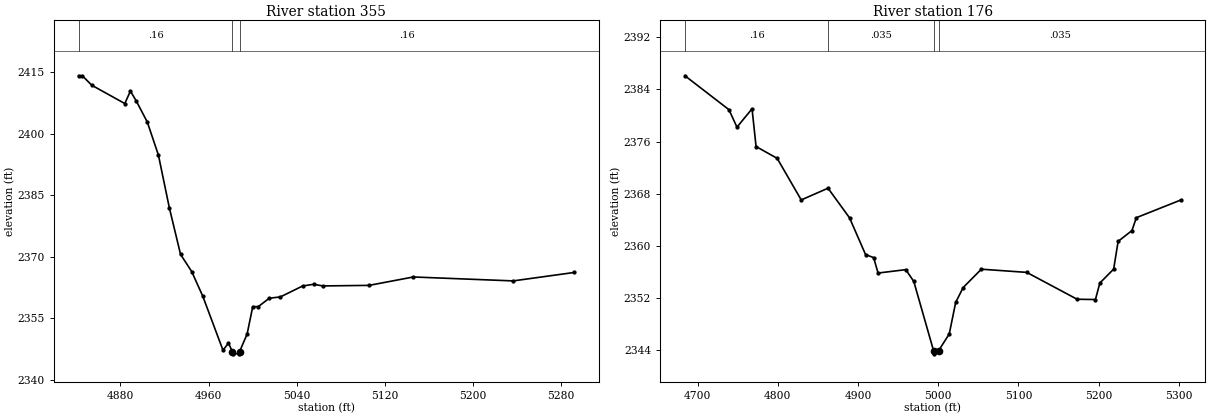
Type RM Length L Ch R = 1 ,355     ,179,179,179
BEGIN DESCRIPTION:
Sweetwater Creek Trib 7 4401
END DESCRIPTION:
XS GIS Cut Line= 3
      1368984.65        6799686.      1369002.71      6799843.06
      1369034.56      6800133.02
#Sta/Elev= 30
  4841.9 2414.18  4845.4 2414.18    4854 2411.86  4883.9  2407.4    4889 2410.44
  4894.2 2408.08  4904.3  2402.9  4914.4 2394.83  4924.4 2381.85  4934.5 2370.57
  4944.6 2366.38  4954.6  2360.4    4973 2347.17    4978 2348.89  4981.6 2346.78
  4982.1 2346.28  4987.5 2346.28    4988 2346.78  4994.9 2351.11    5000  2357.8
    5005  2357.8    5015 2359.86  5025.1 2360.18  5045.2 2362.84  5055.3 2363.27
  5063.5 2362.86  5105.6    2363  5145.8 2365.05  5236.3 2364.09  5291.7 2366.15
#Mann= 3 ,-1 , 0
  4841.9     .16       0  4981.6     .07       0    4988     .16       0
Bank Sta=4981.6,4988
XS Rating Curve= 0 ,0
Exp/Cntr=0.3,0.1

Type RM Length L Ch R = 1 ,176     ,0,0,0
BEGIN DESCRIPTION:
Sweetwater Creek Trib 7 4402
END DESCRIPTION:
XS GIS Cut Line= 3
      1368895.67      6799653.36      1368875.16       6799968.4
       1369004.2      6800241.55
#Sta/Elev= 30
  4684.3 2386.08  4739.1 2380.88  4749.1  2378.2  4767.9 2381.02  4772.9 2375.23
  4799.2 2373.42  4829.2 2367.04  4862.6 2368.84  4889.4  2364.3  4909.4 2358.66
  4919.4  2358.2    4925 2355.83  4959.5 2356.35  4969.5 2354.54  4994.1 2343.94
  4994.6 2343.44  5000.5 2343.94  5013.7 2346.49  5021.7 2351.32    5031  2353.6
  5053.7 2356.42  5110.3 2355.93  5173.1 2351.81  5195.9 2351.77  5201.4  2354.3
  5218.6 2356.43  5224.2 2360.69  5241.4 2362.34  5246.9 2364.32  5302.1 2367.02
#Mann= 4 ,-1 , 0
  4684.3     .16       0  4862.6    .035       0  4994.1    .035       0
  5000.5    .035       0
Bank Sta=4994.1,5000.5
XS Rating Curve= 0 ,0
Exp/Cntr=0.3,0.1

Chan Stop Cuts=-1
Use User Specified Reach Order=0
Composite Channel Slope=5