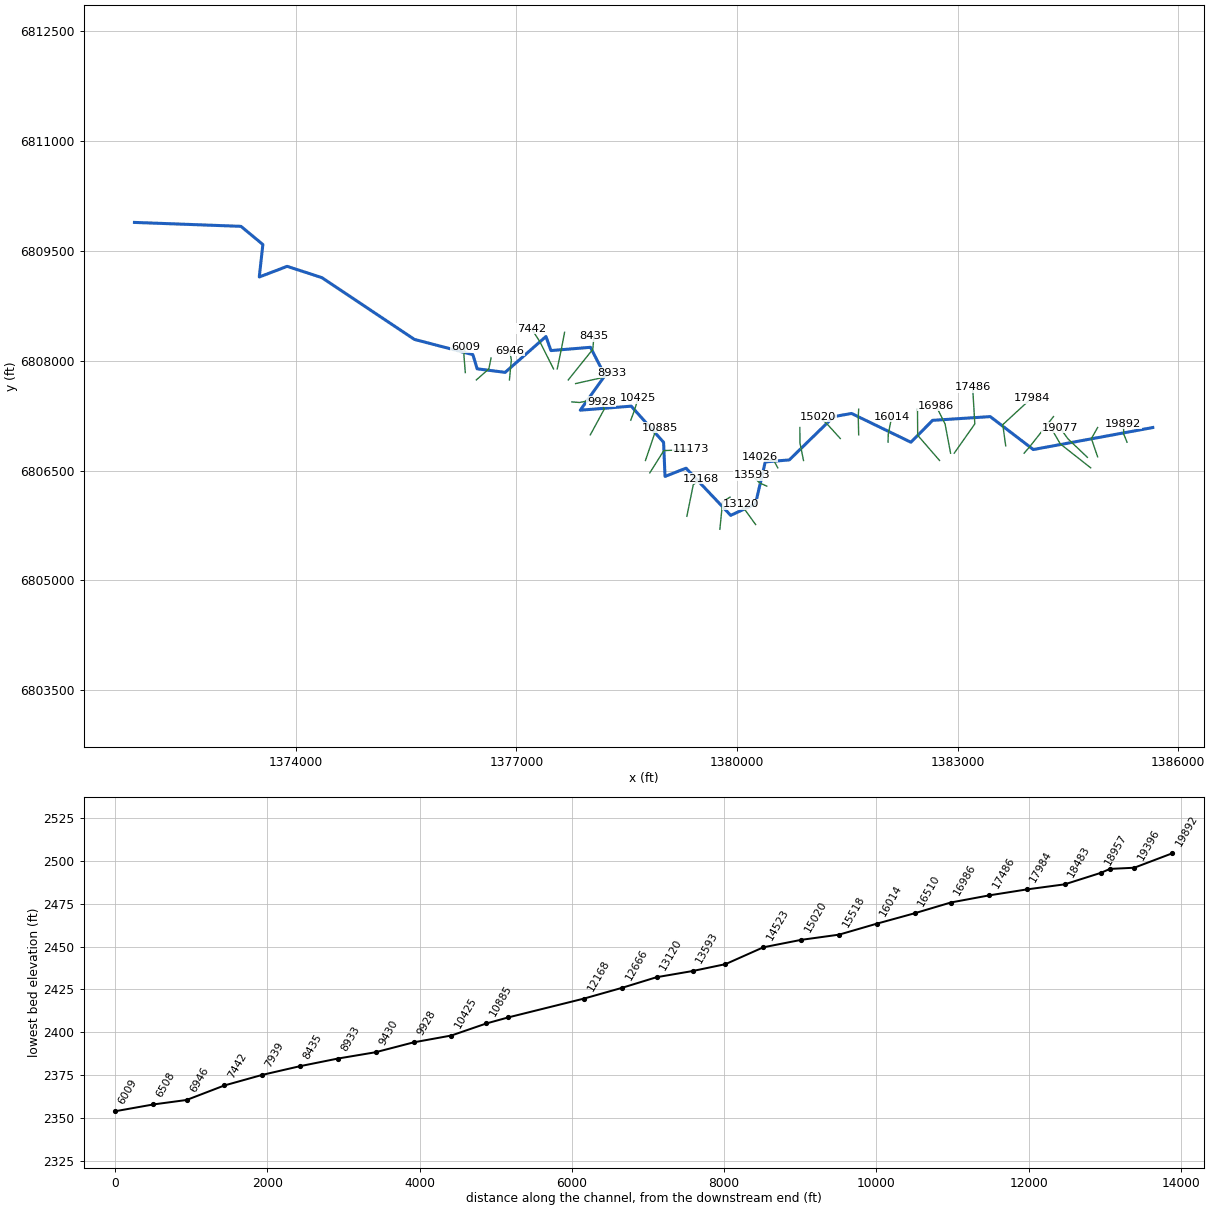
--- Sweetwater Creek Trib 8.prj (project) ---

Proj Title=Sweetwater Creek Trib 8 Base Level Engineering
Current Plan=p01
Default Exp/Contr=0.3,0.1
English Units
Geom File=g01
Flow File=f01
Plan File=p01
Y Axis Title=Elevation
X Axis Title(PF)=Main Channel Distance
X Axis Title(XS)=Station
BEGIN DESCRIPTION:
Sweetwater Creek Trib 8
END DESCRIPTION:
DSS Export Rating Curves= 0
DSS Export Rating Curve Sorted= 0
DSS Export Volume Flow Curves= 0
DXF OffsetX= 0
DXF OffsetY= 0
DXF ScaleX= 1
DXF ScaleY= 10

--- Sweetwater Creek Trib 8.p01 (plan) ---

Plan Title=Multiple Run
Short Identifier=Multiple
Geom File=g01
Flow File=f01
Subcritical Flow
K Sum by GR= 0
Std Step Tol= 0.01
Critical Tol= 0.01
Num of Std Step Trials= 20
Max Error Tol= 0.3
Flow Tol Ratio= 0.001
Split Flow NTrial= 30
Split Flow Tol= 0.02
Split Flow Ratio= 0.02
Log Output Level= 0
Friction Slope Method= 1
Unsteady Friction Slope Method= 2
Unsteady Bridges Friction Slope Method= 1
Parabolic Critical Depth
Global Vel Dist=  1 , 1 , 1
Global Log Level= 0
CheckData=True
Encroach Param= -1, 0, 0, 0
BEGIN DESCRIPTION:
Multiple Run
END DESCRIPTION:

--- Sweetwater Creek Trib 8.f01 (steady flow) ---

Flow Title=Multiple
Program Version=4.10
Number of Profiles= 7
Profile Names=10-year,25-year,50-year,1pct_min,100-year,1pct_plu,500-year
River Rch & RM=Sweetwater Creek,Reach-1         ,19892
     269     378     469     289     576    1150     883
River Rch & RM=Sweetwater Creek,Reach-1         ,19396
     480     699     889     561    1119    2233    1798
River Rch & RM=Sweetwater Creek,Reach-1         ,13593
     655     971    1249     797    1591    3175    2616
River Rch & RM=Sweetwater Creek,Reach-1         ,4520
     698    1044    1351     868    1731    3454    2881
Boundary for River Rch & Prof#=Sweetwater Creek,Reach-1         , 1
Up Type= 0
Dn Type= 3
Dn Slope=0.012
Boundary for River Rch & Prof#=Sweetwater Creek,Reach-1         , 2
Up Type= 0
Dn Type= 3
Dn Slope=0.012
Boundary for River Rch & Prof#=Sweetwater Creek,Reach-1         , 3
Up Type= 0
Dn Type= 3
Dn Slope=0.012
Boundary for River Rch & Prof#=Sweetwater Creek,Reach-1         , 4
Up Type= 0
Dn Type= 3
Dn Slope=0.012
Boundary for River Rch & Prof#=Sweetwater Creek,Reach-1         , 5
Up Type= 0
Dn Type= 3
Dn Slope=0.012
Boundary for River Rch & Prof#=Sweetwater Creek,Reach-1         , 6
Up Type= 0
Dn Type= 3
Dn Slope=0.012
Boundary for River Rch & Prof#=Sweetwater Creek,Reach-1         , 7
Up Type= 0
Dn Type= 3
Dn Slope=0.012
DSS Import GetInterval= 0
DSS Import GetPeak= 0
DSS Import FillOption= 0

--- Sweetwater Creek Trib 8.g01 (geometry) ---

Geom Title=Existing Conditions
Program Version=4.10

River Reach=Sweetwater Creek,Reach-1
Reach XY= 30
        1385655.        6807088.      1384029.91      6806787.79
      1383444.55      6807237.16      1382661.03      6807186.38
      1382365.25      6806887.48      1381558.32      6807279.96
      1381315.44      6807236.94      1380711.21       6806645.8
      1380384.35       6806618.6      1380251.77      6806046.01
      1379914.44      6805889.13      1379307.54      6806533.04
      1379021.25      6806420.76      1379001.46      6806886.54
      1378561.34      6807379.98      1377868.32      6807324.67
      1378203.91      6807797.64      1378007.58      6808183.03
      1377469.45      6808138.63      1377401.88      6808330.49
      1376847.01      6807841.21      1376466.49      6807889.49
      1376407.74      6808082.65      1375612.96      6808291.01
      1374353.53      6809134.45       1373882.2      6809288.39
      1373502.42      6809142.97      1373551.55      6809586.51
       1373253.5      6809834.39        1371805.        6809888.

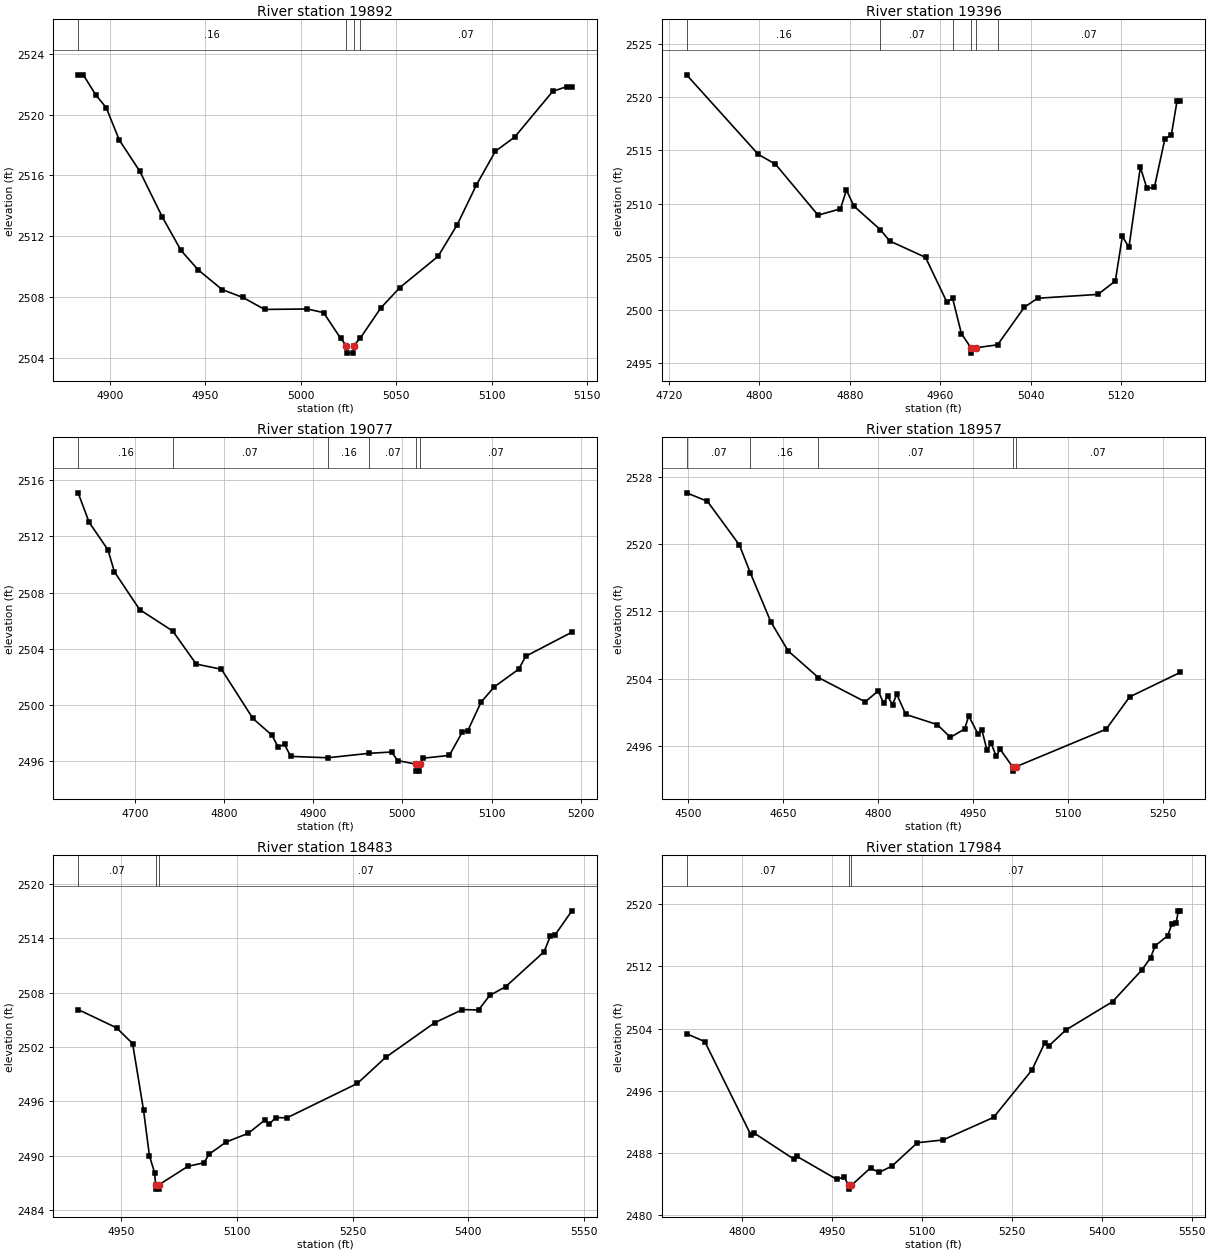
Type RM Length L Ch R = 1 ,19892   ,496,496,496
BEGIN DESCRIPTION:
Sweetwater Creek Trib 8 39.0
END DESCRIPTION:
XS GIS Cut Line= 3
      1385304.99      6806888.03      1385261.05      6806996.15
        1385255.      6807138.02
#Sta/Elev= 30
  4883.3 2522.61    4886 2522.61  4892.6 2521.28    4898 2520.46  4904.9 2518.32
  4915.6 2516.28  4927.5 2513.25  4937.2 2511.08  4946.2  2509.8  4958.8  2508.5
  4969.6 2507.99    4981  2507.2  5003.4 2507.23  5011.9 2506.99  5020.8 2505.31
  5023.8 2504.83    5024 2504.33  5027.5 2504.33  5027.8 2504.83  5031.2 2505.33
  5041.9  2507.3  5051.9 2508.64  5071.9 2510.69  5081.9 2512.76  5091.9 2515.36
  5101.9 2517.59    5112 2518.52    5132 2521.53  5139.5 2521.84    5142 2521.84
#Mann= 4 ,-1 , 0
  4883.3     .16       0  5023.8     .07       0  5027.8     .16       0
  5031.2     .07       0
Bank Sta=5023.8,5027.8
XS Rating Curve= 0 ,0
Exp/Cntr=0.3,0.1

Type RM Length L Ch R = 1 ,19396   ,319,319,319
BEGIN DESCRIPTION:
Sweetwater Creek Trib 8 38.0
END DESCRIPTION:
XS GIS Cut Line= 3
      1384905.01      6806687.97      1384820.06      6806938.14
      1384905.02      6807088.03
#Sta/Elev= 30
  4735.8 2522.09  4799.2 2514.62  4814.3 2513.71    4852 2508.92  4871.8 2509.51
  4877.1 2511.27  4883.7 2509.77  4907.1 2507.55  4915.4 2506.49    4947 2504.96
    4966 2500.74  4970.9 2501.13  4978.7 2497.81  4987.1 2496.47  4987.4 2495.97
  4991.4 2496.47  5010.7 2496.75  5034.3 2500.27    5046 2501.12  5099.4 2501.48
  5114.8 2502.74    5121 2506.93  5126.8  2505.9  5136.9 2513.42  5142.7 2511.44
  5149.3 2511.52  5158.6 2516.09  5164.3 2516.44  5169.4 2519.68  5172.3 2519.68
#Mann= 6 ,-1 , 0
  4735.8     .16       0  4907.1     .07       0  4970.9     .16       0
  4987.1     .07       0  4991.4     .16       0  5010.7     .07       0
Bank Sta=4987.1,4991.4
XS Rating Curve= 0 ,0
Exp/Cntr=0.3,0.1

Type RM Length L Ch R = 1 ,19077   ,120,120,120
BEGIN DESCRIPTION:
Sweetwater Creek Trib 8 4157
END DESCRIPTION:
XS GIS Cut Line= 3
      1384765.67      6806681.31      1384502.55      6806932.54
      1384390.66      6807086.35
#Sta/Elev= 30
  4636.2  2515.1  4648.6    2513  4669.7 2511.04  4676.9 2509.48  4705.2 2506.79
  4742.4 2505.26  4768.7 2502.91    4797 2502.54  4832.3 2499.04  4853.6 2497.85
  4860.6 2497.02  4867.8 2497.19  4874.7 2496.34  4916.3 2496.24    4963 2496.56
  4987.9 2496.65  4994.8 2496.04  5014.9 2495.79  5015.2 2495.29  5019.1 2495.29
  5019.4 2495.79  5023.3 2496.21  5052.7 2496.41  5067.4 2498.09  5073.5 2498.18
  5088.2 2500.19  5102.9 2501.28  5130.4 2502.54  5138.5 2503.47  5190.2 2505.18
#Mann= 6 ,-1 , 0
  4636.2     .16       0  4742.4     .07       0  4916.3     .16       0
    4963     .07       0  5014.9     .07       0  5019.4     .07       0
Bank Sta=5014.9,5019.4
XS Rating Curve= 0 ,0
Exp/Cntr=0.3,0.1

Type RM Length L Ch R = 1 ,18957   ,474,474,474
BEGIN DESCRIPTION:
Sweetwater Creek Trib 8 37.0
END DESCRIPTION:
XS GIS Cut Line= 3
      1384810.83      6806537.67      1384398.33      6806863.57
      1384270.02      6807083.01
#Sta/Elev= 30
  4497.4 2526.11  4530.3  2525.1  4580.8  2519.9  4598.3 2516.54  4630.5 2510.74
  4657.8 2507.29  4705.5 2504.12  4779.5 2501.23  4800.3 2502.54  4808.4 2501.05
  4814.8 2501.91  4822.8 2500.88  4829.2 2502.15  4843.6 2499.73  4893.3 2498.52
  4914.1    2497  4936.6    2498    4943 2499.56  4957.5 2497.42  4963.8 2497.86
  4971.9 2495.46  4978.3  2496.3  4986.3 2494.79  4992.7 2495.57  5012.4 2493.48
  5012.7 2492.98  5016.9 2493.48    5160 2497.97  5197.2 2501.82  5277.3 2504.74
#Mann= 5 ,-1 , 0
  4497.4     .07       0  4598.3     .16       0  4705.5     .07       0
  5012.4     .07       0  5016.9     .07       0
Bank Sta=5012.4,5016.9
XS Rating Curve= 0 ,0
Exp/Cntr=0.3,0.1

Type RM Length L Ch R = 1 ,18483   ,499,499,499
BEGIN DESCRIPTION:
Sweetwater Creek Trib 8 36.0
END DESCRIPTION:
XS GIS Cut Line= 3
      1383905.01      6806738.01      1383974.88      6806817.72
      1384304.98      6807237.98
#Sta/Elev= 30
    4894 2506.14  4943.8 2504.12  4964.7 2502.38  4978.9    2495  4986.5 2489.97
  4993.2 2488.12  4994.5  2486.8  4994.9  2486.3  4998.9  2486.3  4999.2  2486.8
  5036.4 2488.82  5057.2 2489.21  5063.9 2490.16  5086.1 2491.51  5114.8 2492.47
  5135.8 2493.91  5142.2 2493.51  5150.3 2494.21  5164.7 2494.17  5256.1 2497.97
  5292.8 2500.85  5356.4 2504.68  5392.5 2506.13  5413.3 2506.09  5427.8 2507.69
  5448.6 2508.67  5498.3 2512.52  5506.4 2514.24  5512.8 2514.41  5534.4 2517.04
#Mann= 3 ,-1 , 0
    4894     .07       0  4994.5     .07       0  4999.2     .07       0
Bank Sta=4994.5,4999.2
XS Rating Curve= 0 ,0
Exp/Cntr=0.3,0.1

Type RM Length L Ch R = 1 ,17984   ,498,498,498
BEGIN DESCRIPTION:
Sweetwater Creek Trib 8 35.0
END DESCRIPTION:
XS GIS Cut Line= 3
        1383655.      6806838.03      1383614.74      6807127.45
      1384004.98      6807487.99
#Sta/Elev= 30
  4707.8 2503.33  4738.1 2502.33  4815.2 2490.27  4820.3 2490.55  4886.8 2487.18
  4891.9 2487.54  4958.5 2484.57  4970.3  2484.9    4978 2483.82  4978.3 2483.32
  4982.8 2483.82  5014.5 2486.05  5028.7 2485.47  5050.2 2486.28  5092.7  2489.3
  5135.3 2489.65  5219.7 2492.56  5283.8 2498.67  5304.8 2502.12  5312.2 2501.79
  5340.5 2503.83  5418.2 2507.47  5467.5 2511.59  5481.7 2513.14  5489.1 2514.66
  5510.1 2515.96  5517.4 2517.53  5524.2 2517.62  5527.9 2519.17  5531.3 2519.17
#Mann= 3 ,-1 , 0
  4707.8     .07       0    4978     .07       0  4982.8     .07       0
Bank Sta=4978,4982.8
XS Rating Curve= 0 ,0
Exp/Cntr=0.3,0.1

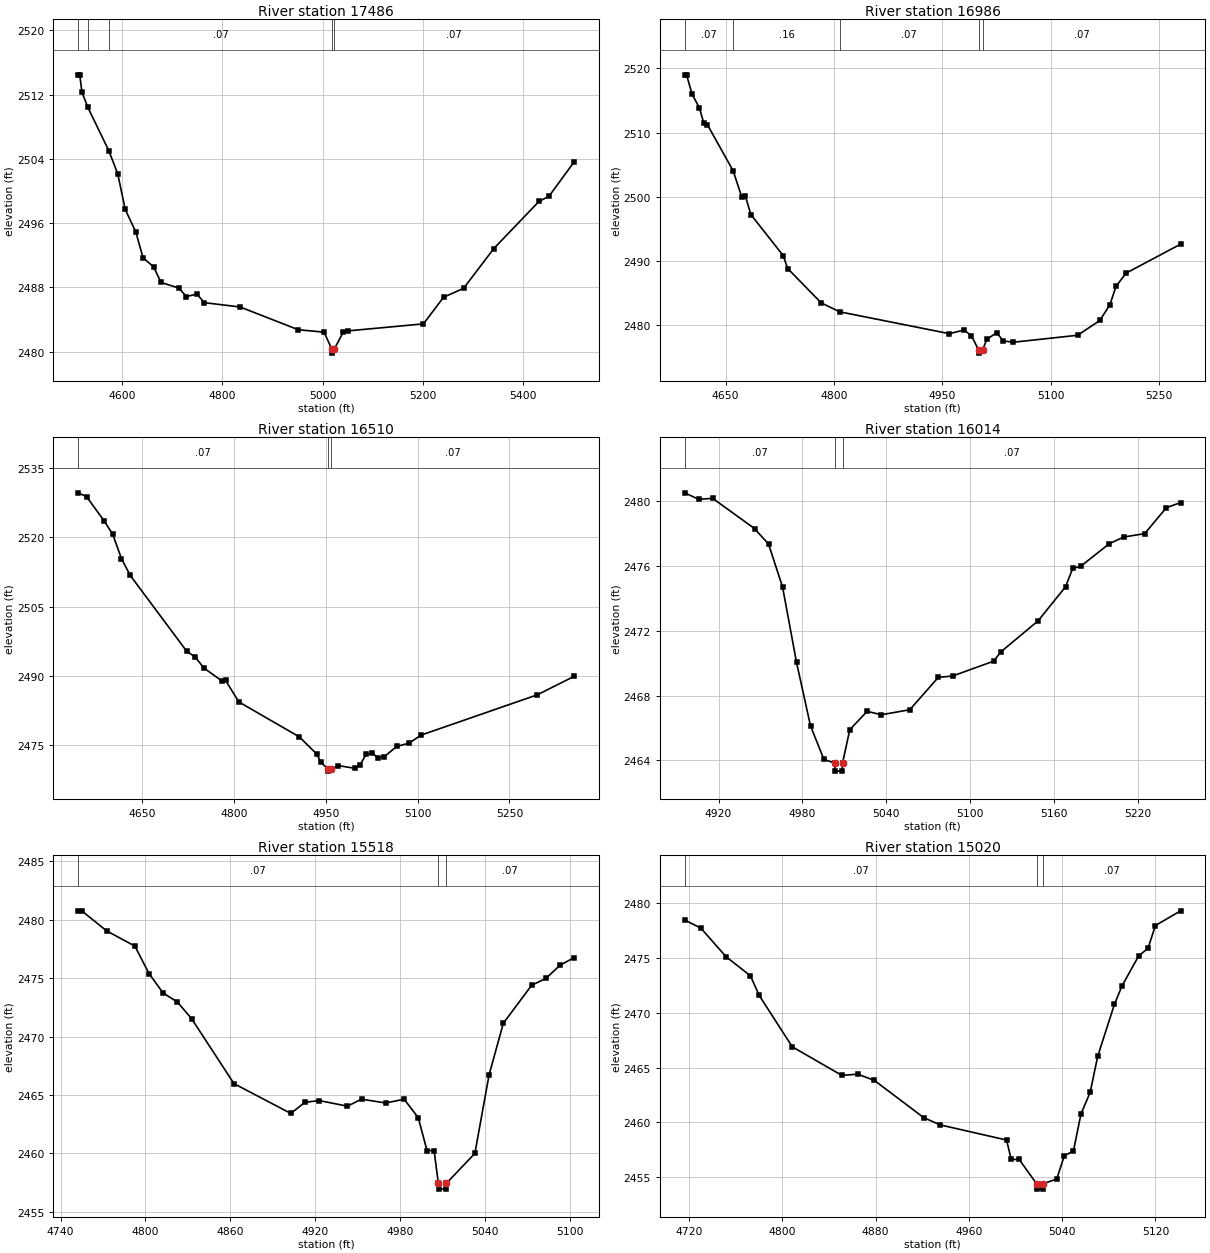
Type RM Length L Ch R = 1 ,17486   ,500,500,500
BEGIN DESCRIPTION:
Sweetwater Creek Trib 8 34.0
END DESCRIPTION:
XS GIS Cut Line= 3
      1382955.02      6806738.03      1383234.68      6807137.21
        1383205.      6807638.04
#Sta/Elev= 30
  4512.6 2514.45  4515.6 2514.45    4520 2512.31  4531.5 2510.44  4573.8 2504.99
  4591.5 2502.12  4606.3  2497.7  4627.2 2494.94    4642 2491.68  4662.9 2490.56
  4677.8 2488.62  4713.5 2487.91  4728.3 2486.86  4749.3 2487.16  4764.1  2486.1
  4835.6 2485.56  4951.5 2482.73  5002.9 2482.43  5018.4 2480.32  5018.7 2479.82
  5023.3 2480.32  5040.9  2482.4  5050.9 2482.59  5201.1 2483.46  5241.2 2486.77
  5281.3 2487.89  5341.4 2492.83  5431.5 2498.69  5451.6 2499.35  5501.7 2503.62
#Mann= 5 ,-1 , 0
  4512.6     .07       0  4531.5     .16       0  4573.8     .07       0
  5018.4     .07       0  5023.3     .07       0
Bank Sta=5018.4,5023.3
XS Rating Curve= 0 ,0
Exp/Cntr=0.3,0.1

Type RM Length L Ch R = 1 ,16986   ,476,476,476
BEGIN DESCRIPTION:
Sweetwater Creek Trib 8 33.0
END DESCRIPTION:
XS GIS Cut Line= 3
      1382905.01      6806737.97        1382830.      6807137.59
      1382704.99      6807388.02
#Sta/Elev= 30
  4593.4    2519    4596    2519  4603.6 2516.01  4613.8 2513.84  4619.7 2511.54
  4624.8 2511.24  4660.4 2504.09  4672.2 2500.06  4677.3 2500.17    4685 2497.26
  4729.9 2490.85  4735.9 2488.86  4782.4 2483.51    4808 2482.12  4959.7 2478.72
  4980.1 2479.28  4990.2 2478.41  5000.3 2476.19  5000.7 2475.69  5005.8 2476.19
  5011.6 2477.83  5025.4 2478.89    5034 2477.61  5047.8 2477.38  5137.3 2478.47
  5168.1 2480.77    5182 2483.22  5190.5 2486.08  5204.4 2488.14  5279.9 2492.65
#Mann= 5 ,-1 , 0
  4593.4     .07       0  4660.4     .16       0    4808     .07       0
  5000.3     .07       0  5005.8     .07       0
Bank Sta=5000.3,5005.8
XS Rating Curve= 0 ,0
Exp/Cntr=0.3,0.1

Type RM Length L Ch R = 1 ,16510   ,496,496,496
BEGIN DESCRIPTION:
Sweetwater Creek Trib 8 32.0
END DESCRIPTION:
XS GIS Cut Line= 3
      1382754.98      6806638.03      1382457.66      6806982.32
        1382455.      6807338.01
#Sta/Elev= 30
  4545.1 2529.61  4558.8 2528.77  4587.3 2523.58  4601.6 2520.61  4615.8 2515.37
  4630.1 2511.75  4722.2 2495.37  4736.5 2494.05  4750.7 2491.69  4779.3 2488.97
  4785.9 2489.03  4807.8 2484.36  4906.5 2476.81    4935  2473.1  4941.6 2471.33
  4953.1  2469.9  4953.6  2469.4  4958.6  2469.9  4970.1  2470.6  4998.2 2469.99
  5005.7 2470.71  5015.7 2473.04  5025.7 2473.26  5035.7 2472.23  5045.7 2472.56
  5065.7 2474.75  5085.7 2475.45  5105.7  2477.2  5295.7 2485.92  5355.7 2489.91
#Mann= 3 ,-1 , 0
  4545.1     .07       0  4953.1     .07       0  4958.6     .07       0
Bank Sta=4953.1,4958.6
XS Rating Curve= 0 ,0
Exp/Cntr=0.3,0.1

Type RM Length L Ch R = 1 ,16014   ,496,496,496
BEGIN DESCRIPTION:
Sweetwater Creek Trib 8 31.0
END DESCRIPTION:
XS GIS Cut Line= 3
        1382055.      6806888.03      1382056.75      6806992.22
        1382105.      6807238.02
#Sta/Elev= 30
  4895.8 2480.52  4905.8 2480.12  4915.8 2480.18  4945.8 2478.31  4955.8 2477.35
  4965.8 2474.71  4975.8 2470.05  4985.8 2466.13  4995.4 2464.06    5003 2463.84
  5003.5 2463.34  5008.3 2463.34  5008.7 2463.84  5013.9  2465.9  5026.3 2467.03
  5036.5 2466.82  5056.8 2467.13  5077.2 2469.13  5087.4 2469.21  5116.8 2470.13
  5121.9  2470.7  5148.6 2472.62  5168.2 2474.72  5173.3 2475.85  5179.1 2475.99
  5199.5 2477.38  5209.7 2477.79  5224.8    2478  5240.3  2479.6  5250.5 2479.92
#Mann= 3 ,-1 , 0
  4895.8     .07       0    5003     .07       0  5008.7     .07       0
Bank Sta=5003,5008.7
XS Rating Curve= 0 ,0
Exp/Cntr=0.3,0.1

Type RM Length L Ch R = 1 ,15518   ,498,498,498
BEGIN DESCRIPTION:
Sweetwater Creek Trib 8 30.0
END DESCRIPTION:
XS GIS Cut Line= 3
        1381655.      6806987.99      1381649.36      6807235.42
        1381655.      6807337.97
#Sta/Elev= 30
  4752.5 2480.76    4755 2480.76  4772.5 2479.05  4792.5 2477.74  4802.5 2475.39
  4812.5 2473.72  4822.5 2472.96  4832.5 2471.54  4862.5 2465.97  4902.6 2463.42
  4912.6 2464.37  4922.6 2464.52  4942.6 2464.04  4952.6 2464.64  4969.7 2464.31
  4982.6 2464.64  4992.6 2463.06  4998.8 2460.24  5003.8 2460.24  5006.8 2457.44
  5007.3 2456.94  5012.1 2456.94  5012.5 2457.44  5032.6    2460  5042.6 2466.71
  5052.7 2471.14  5072.7 2474.39  5082.7 2474.97  5092.7  2476.1  5102.7 2476.76
#Mann= 3 ,-1 , 0
  4752.5     .07       0  5006.8     .07       0  5012.5     .07       0
Bank Sta=5006.8,5012.5
XS Rating Curve= 0 ,0
Exp/Cntr=0.3,0.1

Type RM Length L Ch R = 1 ,15020   ,497,497,497
BEGIN DESCRIPTION:
Sweetwater Creek Trib 8 29.0
END DESCRIPTION:
XS GIS Cut Line= 3
      1381405.01      6806937.99      1381214.74      6807148.55
      1381104.98      6807238.02
#Sta/Elev= 30
  4716.2 2478.46  4730.1 2477.72  4751.7 2475.11  4772.6 2473.37  4780.1 2471.58
  4808.5 2466.89    4851 2464.28  4864.6 2464.39  4878.8 2463.83  4921.3 2460.42
  4935.5 2459.76  4992.3 2458.38  4996.3 2456.61  5003.1 2456.61    5018  2454.4
  5018.5  2453.9  5023.4  2453.9  5023.8  2454.4  5035.3 2454.82  5041.8 2456.93
  5049.7  2457.4  5056.1 2460.75    5064 2462.73  5070.5 2466.03  5084.8 2470.76
  5091.3 2472.44  5105.7  2475.2  5113.6 2475.87    5120 2477.96  5141.6  2479.3
#Mann= 3 ,-1 , 0
  4716.2     .07       0    5018     .07       0  5023.8     .07       0
Bank Sta=5018,5023.8
XS Rating Curve= 0 ,0
Exp/Cntr=0.3,0.1

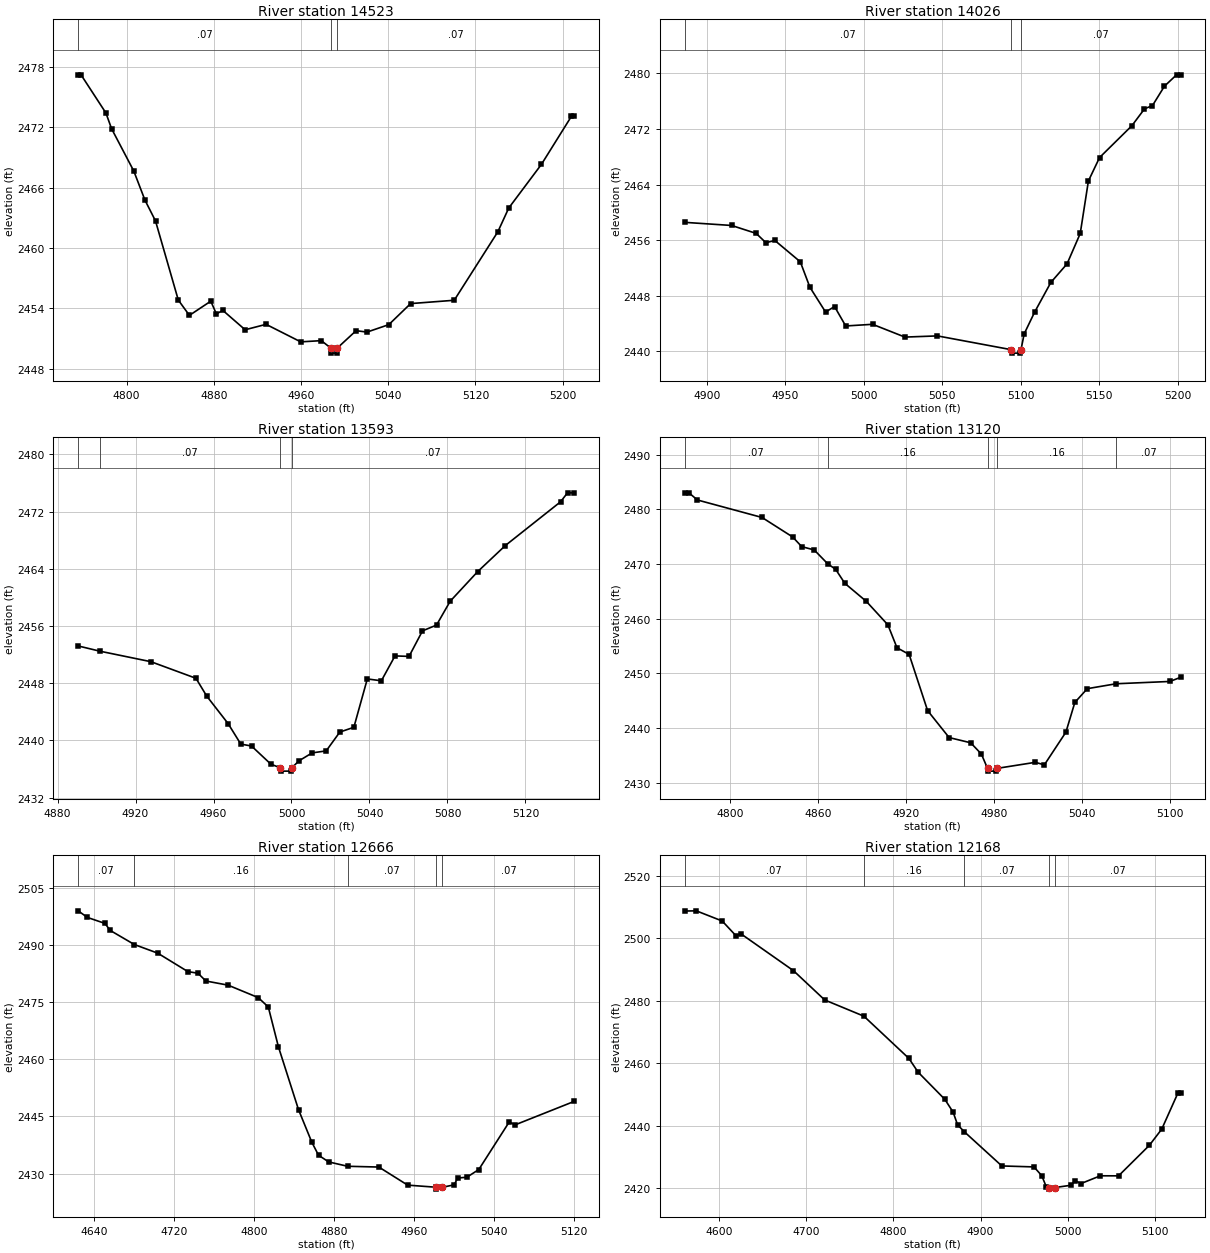
Type RM Length L Ch R = 1 ,14523   ,497,497,497
BEGIN DESCRIPTION:
Sweetwater Creek Trib 8 28.0
END DESCRIPTION:
XS GIS Cut Line= 3
        1380905.      6806637.99      1380856.46      6806877.52
        1380855.      6807088.02
#Sta/Elev= 30
  4755.6  2477.2  4758.2  2477.2    4781 2473.41  4786.2 2471.85  4806.6 2467.64
  4816.8 2464.76  4826.5 2462.69  4847.4 2454.83  4857.6 2453.31  4877.2 2454.72
  4882.3 2453.46  4888.3  2453.8  4908.7 2451.88  4927.9 2452.42  4959.7 2450.68
  4978.6  2450.8  4987.3 2450.06  4987.8 2449.56  4992.7 2449.56  4993.2 2450.06
  5010.5 2451.79  5020.5 2451.65  5040.5 2452.39  5060.5 2454.48  5100.5 2454.81
  5140.5 2461.61  5150.5 2463.97  5180.5 2468.31    5208 2473.08  5210.5 2473.08
#Mann= 3 ,-1 , 0
  4755.6     .07       0  4987.3     .07       0  4993.2     .07       0
Bank Sta=4987.3,4993.2
XS Rating Curve= 0 ,0
Exp/Cntr=0.3,0.1

Type RM Length L Ch R = 1 ,14026   ,433,433,433
BEGIN DESCRIPTION:
Sweetwater Creek Trib 8 27.0
END DESCRIPTION:
XS GIS Cut Line= 3
      1380554.99      6806538.01      1380500.41       6806638.1
      1380304.98        6806688.
#Sta/Elev= 30
    4886 2458.56  4915.9 2458.11  4931.5 2456.97  4937.7 2455.63  4943.4 2455.95
  4959.6 2452.88  4965.7 2449.22  4975.7 2445.64  4981.4 2446.44  4988.5 2443.64
  5005.6 2443.88  5026.2 2442.04  5046.9 2442.21  5093.8 2440.23  5094.3 2439.73
  5099.6 2439.73  5100.1 2440.23  5102.1  2442.5  5108.8 2445.65  5119.1 2449.91
  5129.4 2452.58  5137.8 2456.96    5143 2464.52  5150.1 2467.89  5170.7 2472.48
  5178.7  2474.9  5183.8 2475.38  5191.4 2478.16  5199.1  2479.8  5201.7  2479.8
#Mann= 3 ,-1 , 0
    4886     .07       0  5093.8     .07       0  5100.1     .07       0
Bank Sta=5093.8,5100.1
XS Rating Curve= 0 ,0
Exp/Cntr=0.3,0.1

Type RM Length L Ch R = 1 ,13593   ,473,473,473
BEGIN DESCRIPTION:
Sweetwater Creek Trib 8 26.0
END DESCRIPTION:
XS GIS Cut Line= 3
      1380404.96      6806288.02      1380305.37       6806333.3
      1380205.03      6806437.97
#Sta/Elev= 30
  4890.6 2453.21  4901.7 2452.48  4927.9 2451.01    4951 2448.69  4956.5 2446.21
  4967.5 2442.35    4974 2439.49  4979.5 2439.22  4989.4 2436.69  4993.9 2436.21
  4994.4 2435.71  4999.8 2435.71  5000.3 2436.21  5003.9 2437.16  5010.6 2438.26
  5017.8 2438.54  5024.8 2441.17    5032 2441.84  5038.9  2448.6  5046.1 2448.34
  5053.1 2451.82  5060.3 2451.75  5067.2 2455.32  5074.4 2456.13  5081.4 2459.46
  5095.5  2463.6  5109.7 2467.25    5138 2473.36  5141.6 2474.62    5145 2474.62
#Mann= 4 ,-1 , 0
  4890.6     .16       0  4901.7     .07       0  4993.9     .07       0
  5000.3     .07       0
Bank Sta=4993.9,5000.3
XS Rating Curve= 0 ,0
Exp/Cntr=0.3,0.1

Type RM Length L Ch R = 1 ,13120   ,454,454,454
BEGIN DESCRIPTION:
Sweetwater Creek Trib 8 25.0
END DESCRIPTION:
XS GIS Cut Line= 3
      1380253.44      6805763.72      1380118.38      6805951.24
      1380055.03      6806037.96
#Sta/Elev= 30
  4768.9 2483.04  4771.8 2483.04  4777.6 2481.73  4821.7 2478.53  4842.6 2474.96
  4848.8 2473.19  4857.3 2472.59  4866.4 2470.09    4872 2469.02  4878.2 2466.48
  4892.9 2463.17  4907.6 2458.88  4913.8 2454.69  4922.1 2453.47  4934.7 2443.19
  4949.4 2438.25  4964.1  2437.3  4971.4 2435.24  4975.6 2432.61  4976.1 2432.11
  4981.5 2432.11    4982 2432.61  5008.2 2433.72  5014.4 2433.26  5029.1 2439.24
  5035.2 2444.68  5043.7  2447.2  5063.4  2448.1  5100.1 2448.52  5107.4 2449.28
#Mann= 5 ,-1 , 0
  4768.9     .07       0  4866.4     .16       0  4975.6     .07       0
    4982     .16       0  5063.4     .07       0
Bank Sta=4975.6,4982
XS Rating Curve= 0 ,0
Exp/Cntr=0.3,0.1

Type RM Length L Ch R = 1 ,12666   ,498,498,498
BEGIN DESCRIPTION:
Sweetwater Creek Trib 8 24.0
END DESCRIPTION:
XS GIS Cut Line= 3
      1379767.09      6805698.93      1379804.24      6806072.79
      1379904.98      6806137.99
#Sta/Elev= 30
  4624.3    2499  4633.4 2497.27  4651.1 2495.69  4656.1 2493.88  4680.4 2490.15
  4703.8 2487.88  4733.9 2483.04    4744 2482.61  4751.9 2480.57  4774.1 2479.48
  4804.3  2476.2  4814.3 2473.74  4824.4  2463.3  4844.5 2446.78  4857.8 2438.22
  4864.5 2434.82  4874.6 2433.06  4893.6 2431.91  4924.8 2431.71  4953.6 2426.96
  4981.9 2426.41  4982.4 2425.91  4988.4 2426.41    5000 2427.03  5003.6 2428.82
  5012.8 2429.04  5024.7 2431.06  5055.1 2443.55    5061 2442.79    5120 2448.95
#Mann= 5 ,-1 , 0
  4624.3     .07       0  4680.4     .16       0  4893.6     .07       0
  4981.9     .07       0  4988.4     .07       0
Bank Sta=4981.9,4988.4
XS Rating Curve= 0 ,0
Exp/Cntr=0.3,0.1

Type RM Length L Ch R = 1 ,12168   ,995,995,995
BEGIN DESCRIPTION:
Sweetwater Creek Trib 8 23.0
END DESCRIPTION:
XS GIS Cut Line= 3
      1379318.18      6805875.88       1379405.2      6806306.17
      1379505.03      6806388.03
#Sta/Elev= 30
    4561 2508.66  4574.3 2508.73    4604 2505.47    4620 2500.68  4625.1 2501.44
  4685.6 2489.58  4721.4  2480.2  4766.3 2475.01  4817.8 2461.51  4828.4 2457.09
    4859  2448.4  4868.5 2444.29  4873.6 2440.25  4881.4    2438  4924.3 2427.08
  4961.1 2426.77    4970 2423.98  4975.1 2420.49  4978.2 2420.16  4978.7 2419.66
  4984.8 2420.16  5003.1 2420.88  5008.5 2422.34    5015 2421.45  5037.2 2423.93
    5058 2423.91  5093.2 2433.65  5107.5 2438.87  5125.8 2450.29  5129.1 2450.29
#Mann= 5 ,-1 , 0
    4561     .07       0  4766.3     .16       0  4881.4     .07       0
  4978.2     .07       0  4984.8     .07       0
Bank Sta=4978.2,4984.8
XS Rating Curve= 0 ,0
Exp/Cntr=0.3,0.1

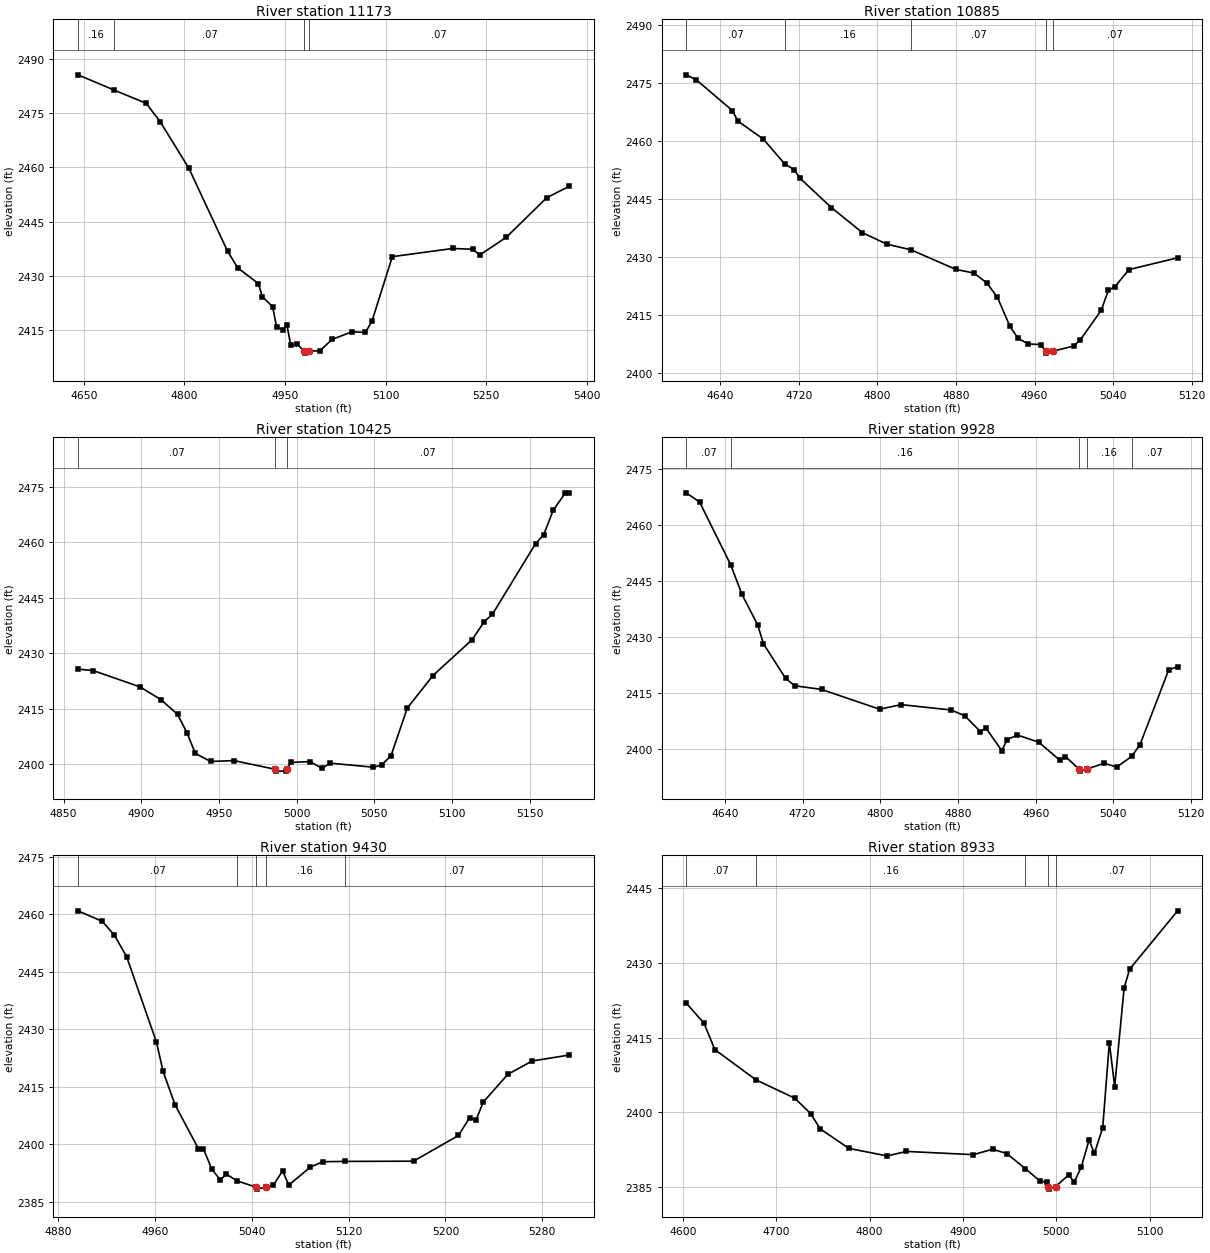
Type RM Length L Ch R = 1 ,11173   ,288,288,288
BEGIN DESCRIPTION:
Sweetwater Creek Trib 8 22.0
END DESCRIPTION:
XS GIS Cut Line= 3
      1378814.35      6806469.44      1379005.04      6806773.02
      1379378.83       6806788.2
#Sta/Elev= 30
  4641.5 2485.53  4695.9 2481.28  4743.2 2477.66  4764.4 2472.48  4806.8 2459.72
  4864.5  2436.8  4879.8 2432.19  4910.4 2427.88  4916.3 2424.28  4931.6 2421.51
  4937.5 2415.93  4946.8 2415.16  4952.8 2416.52  4958.7 2410.84  4968.1 2411.18
  4978.9 2409.18  4979.4 2408.68  4985.6 2409.18  5002.5 2409.37    5020 2412.45
    5050 2414.59    5070 2414.38    5080 2417.68    5110 2435.32  5200.1 2437.58
  5230.1 2437.36  5240.2 2435.76  5280.2 2440.71  5340.2 2451.61  5374.1 2454.79
#Mann= 4 ,-1 , 0
  4641.5     .16       0  4695.9     .07       0  4978.9     .07       0
  4985.6     .07       0
Bank Sta=4978.9,4985.6
XS Rating Curve= 0 ,0
Exp/Cntr=0.3,0.1

Type RM Length L Ch R = 1 ,10885   ,460,460,460
BEGIN DESCRIPTION:
Sweetwater Creek Trib 8 21.0
END DESCRIPTION:
XS GIS Cut Line= 3
      1378755.01      6806638.04      1378881.82      6807011.71
      1378954.99      6807087.99
#Sta/Elev= 30
  4605.4 2477.17  4615.8 2475.86  4652.5 2467.91  4658.2 2465.16  4683.9 2460.55
  4705.8  2454.1  4715.3 2452.62  4721.5 2450.36  4753.2 2442.82  4784.9 2436.31
  4809.5 2433.36  4834.4 2431.87  4879.9 2426.81  4898.4 2425.86  4911.6 2423.27
  4922.2 2419.61    4935 2412.06  4943.3 2408.94  4953.8  2407.5  4966.4 2407.36
  4971.3 2405.64  4971.8 2405.14  4978.7 2405.64    5000 2406.98  5006.8 2408.65
  5027.9 2416.21  5035.1 2421.37    5042 2422.38  5056.2 2426.77  5105.7 2429.81
#Mann= 5 ,-1 , 0
  4605.4     .07       0  4705.8     .16       0  4834.4     .07       0
  4971.3     .07       0  4978.7     .07       0
Bank Sta=4971.3,4978.7
XS Rating Curve= 0 ,0
Exp/Cntr=0.3,0.1

Type RM Length L Ch R = 1 ,10425   ,497,497,497
BEGIN DESCRIPTION:
Sweetwater Creek Trib 8 20.0
END DESCRIPTION:
XS GIS Cut Line= 3
      1378555.02      6807188.04      1378604.57      6807319.73
      1378655.01      6807488.03
#Sta/Elev= 30
  4859.3 2425.67    4869  2425.3  4899.2 2420.88  4912.7 2417.44  4923.4 2413.44
  4929.5 2408.45  4934.8  2402.9  4944.7 2400.72  4959.7 2400.96  4986.2 2398.61
  4986.7 2398.11  4993.2 2398.11  4993.7 2398.61  4996.4 2400.46  5008.6  2400.7
  5016.4 2398.86  5021.6 2400.26  5049.5 2399.17  5054.7 2399.74  5060.8 2402.28
  5071.3 2415.17  5087.8 2423.94    5113 2433.63  5120.8 2438.48  5126.1 2440.52
  5153.9 2459.61  5159.1 2462.01  5165.2  2468.6  5173.1 2473.33  5175.7 2473.33
#Mann= 3 ,-1 , 0
  4859.3     .07       0  4986.2     .07       0  4993.7     .07       0
Bank Sta=4986.2,4993.7
XS Rating Curve= 0 ,0
Exp/Cntr=0.3,0.1

Type RM Length L Ch R = 1 ,9928    ,498,498,498
BEGIN DESCRIPTION:
Sweetwater Creek Trib 8 19.0
END DESCRIPTION:
XS GIS Cut Line= 3
      1378005.01      6806988.01      1378195.22      6807339.66
      1378155.02      6807437.96
#Sta/Elev= 30
  4600.2 2468.65    4614  2466.2    4646 2449.41  4657.7 2441.43  4673.9 2433.24
  4679.8 2428.21  4702.5 2418.99    4712 2416.97  4739.6 2415.99  4799.5 2410.68
  4821.4 2411.92    4873 2410.49    4887 2408.94  4903.2  2404.7  4908.9 2405.62
  4925.1 2399.62  4930.8 2402.58  4941.3 2403.77  4963.2 2401.87    4985 2397.01
  4990.7 2398.02  5004.9 2394.61  5005.4 2394.11  5012.4 2394.61  5030.6 2396.24
  5043.5 2395.19    5059 2398.09  5067.5 2401.22  5096.9 2421.17  5106.2 2422.12
#Mann= 5 ,-1 , 0
  4600.2     .07       0    4646     .16       0  5004.9     .07       0
  5012.4     .16       0    5059     .07       0
Bank Sta=5004.9,5012.4
XS Rating Curve= 0 ,0
Exp/Cntr=0.3,0.1

Type RM Length L Ch R = 1 ,9430    ,497,497,497
BEGIN DESCRIPTION:
Sweetwater Creek Trib 8 18.0
END DESCRIPTION:
XS GIS Cut Line= 3
      1377754.95        6807438.      1377858.14      6807429.95
      1378155.01        6807488.
#Sta/Elev= 30
  4896.5 2460.85  4916.6 2458.11  4926.6 2454.49  4936.7 2448.89  4961.3 2426.67
  4966.8 2419.01  4976.8 2410.23  4995.9 2398.94    5000 2398.94    5007  2393.6
    5014 2390.78  5019.1 2392.25    5028 2390.49  5043.9 2388.86  5044.4 2388.36
  5051.6 2388.86  5057.9 2389.35  5065.5 2393.16  5070.6 2389.42  5088.5  2394.1
  5098.7  2395.5  5116.7 2395.58  5173.7 2395.64  5210.8 2402.34  5220.1 2407.01
  5225.2 2406.25  5231.2    2411  5251.5 2418.24  5271.6 2421.73  5302.5  2423.3
#Mann= 5 ,-1 , 0
  4896.5     .07       0    5028     .16       0  5043.9     .07       0
  5051.6     .16       0  5116.7     .07       0
Bank Sta=5043.9,5051.6
XS Rating Curve= 0 ,0
Exp/Cntr=0.3,0.1

Type RM Length L Ch R = 1 ,8933    ,498,498,498
BEGIN DESCRIPTION:
Sweetwater Creek Trib 8 17.0
END DESCRIPTION:
XS GIS Cut Line= 3
      1377804.97      6807687.99      1378191.66       6807774.7
      1378304.99      6807837.99
#Sta/Elev= 30
  4603.7 2421.93  4622.8 2417.86  4634.5 2412.57  4678.5 2406.53  4719.8 2402.88
    4737 2399.79  4747.2 2396.71    4778 2392.81  4818.9  2391.3  4839.4 2392.21
  4911.2 2391.56  4931.7 2392.65  4946.8 2391.79  4966.9 2388.75  4982.9 2386.19
  4990.1 2386.12  4991.4 2385.16  4991.9 2384.66  4999.1 2385.16  5013.3 2387.52
    5019 2386.04  5026.7  2389.1    5035  2394.5  5040.7 2391.82  5049.6 2396.96
  5056.7 2413.99  5062.4 2405.19  5072.5 2424.93  5078.4 2428.69  5129.8 2440.37
#Mann= 5 ,-1 , 0
  4603.7     .07       0  4678.5     .16       0  4966.9     .07       0
  4991.4     .07       0  4999.1     .07       0
Bank Sta=4991.4,4999.1
XS Rating Curve= 0 ,0
Exp/Cntr=0.3,0.1

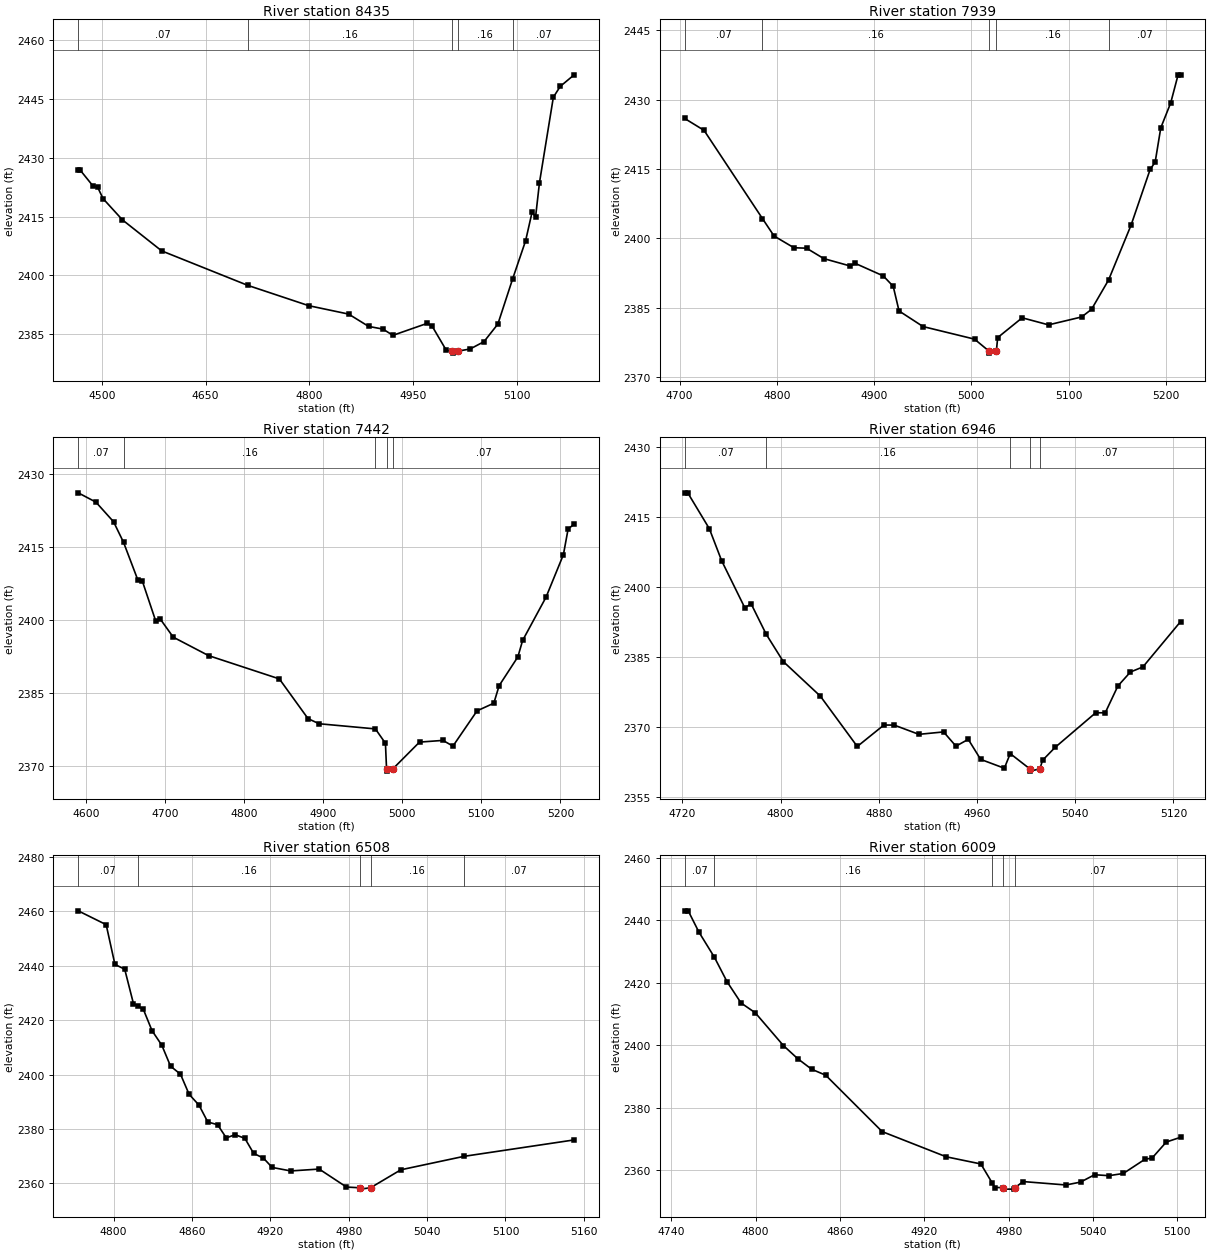
Type RM Length L Ch R = 1 ,8435    ,496,496,496
BEGIN DESCRIPTION:
Sweetwater Creek Trib 8 16.0
END DESCRIPTION:
XS GIS Cut Line= 3
      1377705.03      6807738.04      1378038.73      6808155.31
        1378055.      6808337.99
#Sta/Elev= 30
  4465.7 2426.74  4468.9 2426.74  4487.3 2422.74  4493.7  2422.5  4501.7 2419.55
  4529.7 2414.15  4586.5 2406.25  4710.9 2397.48  4799.4 2392.29  4857.1 2390.15
  4885.9 2387.02  4906.7 2386.33  4921.1 2384.74  4970.7 2387.79  4977.8  2387.1
  4998.5 2380.89  5007.2 2380.71  5007.7 2380.21  5014.9 2380.71  5032.8 2381.26
  5052.9 2383.13    5073 2387.61  5094.4 2399.13  5113.1  2408.8  5122.6 2416.17
  5127.6 2414.93  5133.2 2423.62  5153.3 2445.39  5163.3 2448.15  5183.4 2451.09
#Mann= 5 ,-1 , 0
  4465.7     .07       0  4710.9     .16       0  5007.2     .07       0
  5014.9     .16       0  5094.4     .07       0
Bank Sta=5007.2,5014.9
XS Rating Curve= 0 ,0
Exp/Cntr=0.3,0.1

Type RM Length L Ch R = 1 ,7939    ,497,497,497
BEGIN DESCRIPTION:
Sweetwater Creek Trib 8 15.0
END DESCRIPTION:
XS GIS Cut Line= 3
      1377555.01      6807888.04      1377614.93      6808176.58
        1377655.      6808388.02
#Sta/Elev= 30
  4705.3 2425.94  4725.2 2423.37  4785.3 2404.25  4797.2 2400.49  4817.6 2397.95
  4830.6 2397.85  4848.3  2395.6  4875.6 2393.99  4880.7 2394.56  4909.5 2391.85
  4919.7  2389.6  4925.7 2384.26  4950.4 2380.88  5003.3 2378.16  5017.8 2375.63
  5018.3 2375.13  5025.8 2375.63  5027.1 2378.49  5052.3 2382.78  5079.4 2381.25
  5113.4 2382.96  5123.6 2384.61  5141.1 2390.96  5164.3 2402.87  5183.9 2414.93
    5189 2416.46  5194.8 2423.91    5205 2429.31  5212.6 2435.39  5215.2 2435.39
#Mann= 5 ,-1 , 0
  4705.3     .07       0  4785.3     .16       0  5017.8     .07       0
  5025.8     .16       0  5141.1     .07       0
Bank Sta=5017.8,5025.8
XS Rating Curve= 0 ,0
Exp/Cntr=0.3,0.1

Type RM Length L Ch R = 1 ,7442    ,496,496,496
BEGIN DESCRIPTION:
Sweetwater Creek Trib 8 14.0
END DESCRIPTION:
XS GIS Cut Line= 3
      1377505.01      6807887.98      1377321.68      6808254.71
      1377204.99      6808438.02
#Sta/Elev= 30
    4590 2426.11  4612.4  2424.2  4634.7 2420.17  4647.3 2415.96  4665.5 2408.18
  4671.1 2407.99  4687.9 2399.85  4693.4 2400.28  4710.2 2396.47  4754.9 2392.68
  4844.4  2387.9  4880.7 2379.74  4894.7 2378.69  4965.9 2377.63  4978.6 2374.68
    4980 2369.46  4980.5 2368.96  4988.2 2369.46  5021.7 2374.92  5051.3 2375.27
    5064  2374.1  5094.5 2381.34  5115.7 2382.91  5122.4 2386.51  5146.1 2392.42
  5152.1 2395.79  5181.7 2404.67  5203.7 2413.41  5209.7 2418.71  5217.3 2419.66
#Mann= 5 ,-1 , 0
    4590     .07       0  4647.3     .16       0  4965.9     .07       0
    4980     .07       0  4988.2     .07       0
Bank Sta=4980,4988.2
XS Rating Curve= 0 ,0
Exp/Cntr=0.3,0.1

Type RM Length L Ch R = 1 ,6946    ,438,438,438
BEGIN DESCRIPTION:
Sweetwater Creek Trib 8 13.0
END DESCRIPTION:
XS GIS Cut Line= 3
        1376905.      6807738.03      1376931.27      6808014.88
        1376905.      6808138.01
#Sta/Elev= 30
  4721.9 2420.12  4724.4 2420.12    4742 2412.43    4752 2405.58  4770.9 2395.48
    4776 2396.36  4788.3 2389.83  4802.2 2383.98  4832.4 2376.57  4862.5 2365.78
  4884.2 2370.38  4892.6 2370.36  4912.7 2368.38  4932.8  2368.9  4942.9 2365.85
  4952.9 2367.31    4963 2363.02  4982.3 2361.12  4987.1 2364.25    5003    2361
  5003.5  2360.5  5011.3    2361  5013.4 2362.81  5023.6 2365.57  5056.7    2373
  5064.5    2373  5074.8 2378.74    5085 2381.73  5095.2 2382.83  5125.9 2392.54
#Mann= 5 ,-1 , 0
  4721.9     .07       0  4788.3     .16       0  4987.1     .07       0
    5003     .07       0  5011.3     .07       0
Bank Sta=5003,5011.3
XS Rating Curve= 0 ,0
Exp/Cntr=0.3,0.1

Type RM Length L Ch R = 1 ,6508    ,499,499,499
BEGIN DESCRIPTION:
Sweetwater Creek Trib 8 12.0
END DESCRIPTION:
XS GIS Cut Line= 3
      1376454.97      6807737.97      1376625.14      6807888.35
        1376655.        6808038.
#Sta/Elev= 30
  4772.9 2460.13  4794.3 2455.05    4801 2440.45  4808.5 2438.67  4815.2 2426.02
  4818.6 2425.11  4822.7 2424.02  4829.4 2416.12  4836.9 2410.76  4843.6 2403.06
  4851.2 2400.11  4857.8 2392.73  4865.4 2388.73  4872.1 2382.55  4879.6 2381.56
  4886.3  2376.7    4893  2377.9  4900.5 2376.54  4907.2 2371.03  4914.7 2369.28
  4921.4 2365.86  4935.6 2364.57  4957.4 2365.26  4978.3 2358.65  4988.3 2358.39
  4988.8 2357.89  4996.7 2358.39  5019.9 2364.99  5068.2 2369.93  5152.6 2375.97
#Mann= 5 ,-1 , 0
  4772.9     .07       0  4818.6     .16       0  4988.3     .07       0
  4996.7     .16       0  5068.2     .07       0
Bank Sta=4988.3,4996.7
XS Rating Curve= 0 ,0
Exp/Cntr=0.3,0.1

Type RM Length L Ch R = 1 ,6009    ,492,492,492
BEGIN DESCRIPTION:
Sweetwater Creek Trib 8 11.0
END DESCRIPTION:
XS GIS Cut Line= 3
        1376305.      6807837.98      1376284.86      6808087.67
      1376304.99      6808187.97
#Sta/Elev= 30
  4749.5 2443.07    4752 2443.07  4759.6 2436.28  4770.7 2428.16  4779.6  2420.4
  4789.6 2413.56  4799.7 2410.42  4819.7 2399.93  4829.8 2395.76  4839.8 2392.34
  4849.8 2390.43    4890 2372.36  4935.6 2364.29  4960.2    2362  4968.1 2356.04
  4970.2 2354.46    4976 2354.44  4976.5 2353.94    4984 2353.94  4984.5 2354.44
  4990.3 2356.36  5020.7 2355.27  5031.1 2356.19  5041.1 2358.55  5051.3 2358.25
  5061.5 2358.95  5076.9  2363.5    5082 2363.89  5092.1 2369.02  5102.3 2370.55
#Mann= 5 ,-1 , 0
  4749.5     .07       0  4770.7     .16       0  4968.1     .07       0
    4976     .07       0  4984.5     .07       0
Bank Sta=4976,4984.5
XS Rating Curve= 0 ,0
Exp/Cntr=0.3,0.1