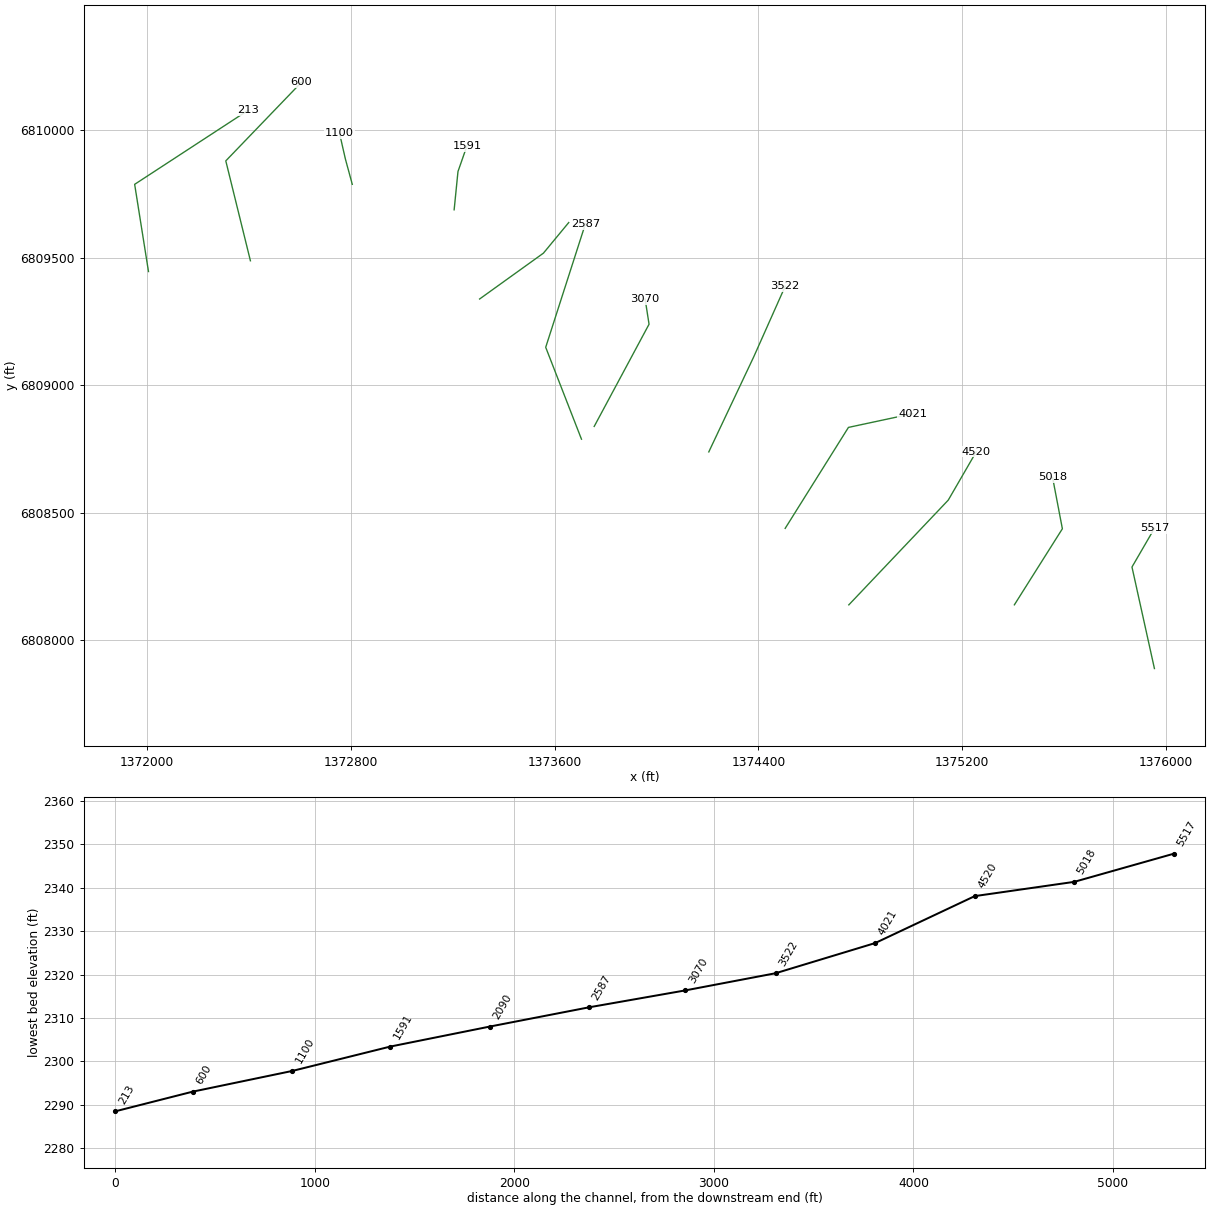
HEC-RAS study Sweetwater Creek Trib 8.prj: Sweetwater Creek Trib 8 Base Level Engineering

--- Sweetwater Creek Trib 8.g01 (geometry) --- (continued)

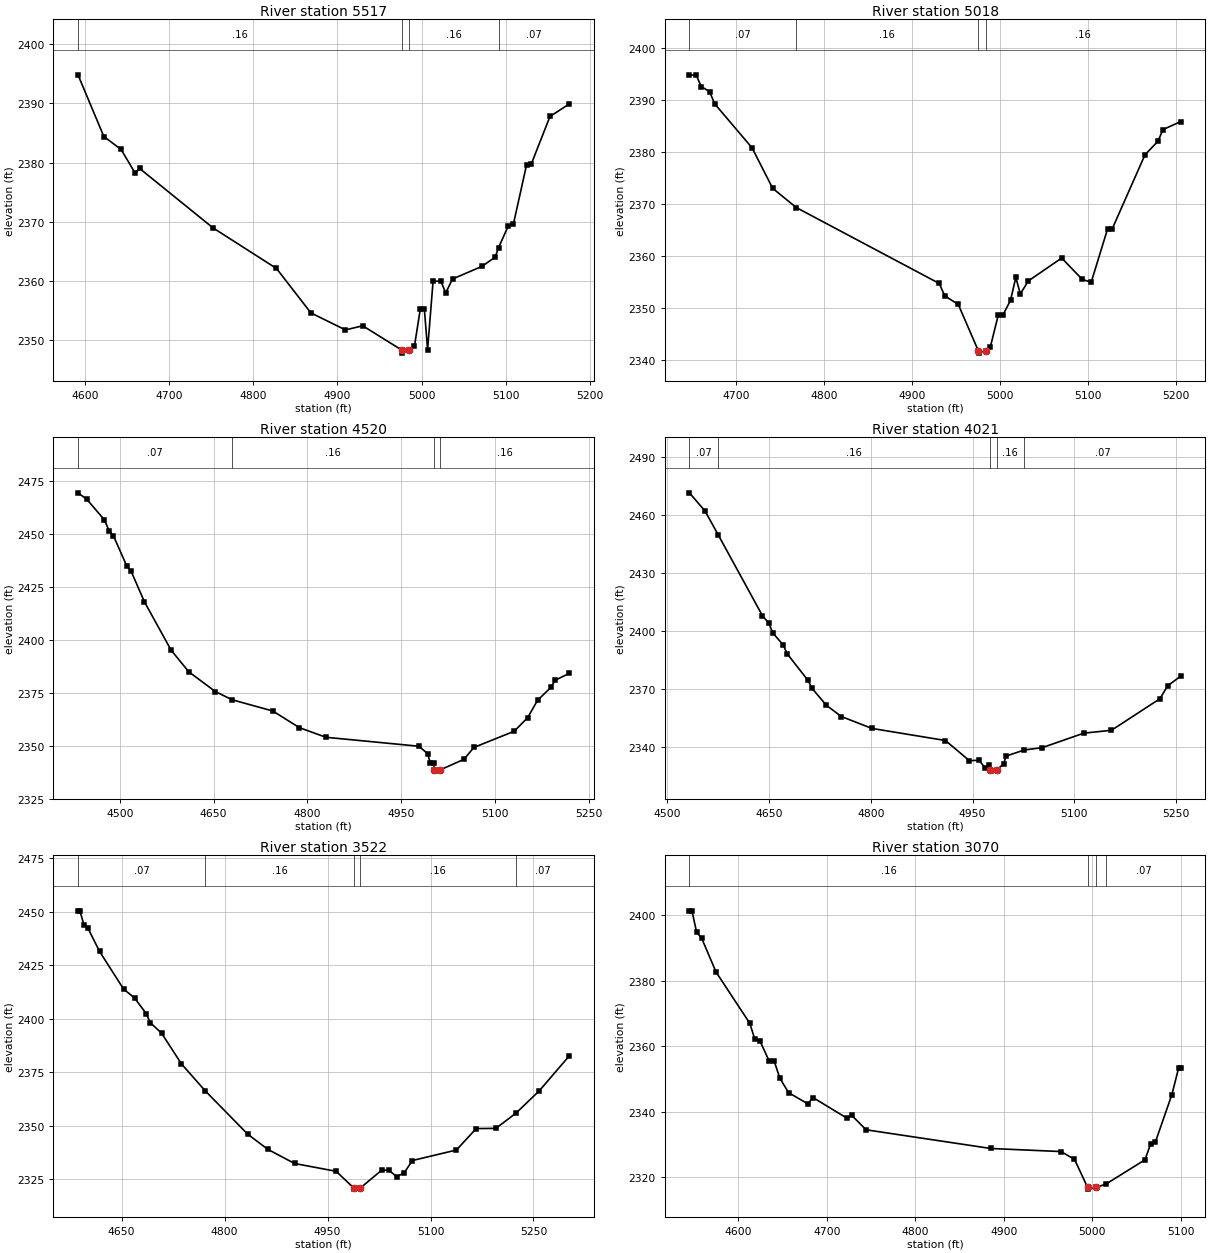
Type RM Length L Ch R = 1 ,5517    ,499,499,499
BEGIN DESCRIPTION:
Sweetwater Creek Trib 8 10.0
END DESCRIPTION:
XS GIS Cut Line= 3
        1375955.      6807887.99      1375866.83      6808286.35
      1375954.99      6808437.98
#Sta/Elev= 30
    4592 2394.83  4622.7 2384.41  4643.2 2382.22    4660 2378.19  4665.1 2379.02
  4752.4 2368.97  4827.6 2362.13  4868.5 2354.62  4909.5 2351.75    4930 2352.45
  4976.5 2348.33    4977 2347.83    4985 2348.33  4991.4 2349.02  4998.3 2355.21
  5003.2 2355.21    5007 2348.44  5013.5 2359.97  5022.7 2359.99  5028.5    2358
  5036.6 2360.35  5071.5 2362.48  5087.3 2364.05  5091.2 2365.64    5103 2369.37
  5108.8 2369.57  5124.5 2379.64  5130.3 2379.84  5152.3  2387.8  5175.4 2389.93
#Mann= 4 ,-1 , 0
    4592     .16       0  4976.5     .07       0    4985     .16       0
  5091.2     .07       0
Bank Sta=4976.5,4985
XS Rating Curve= 0 ,0
Exp/Cntr=0.3,0.1

Type RM Length L Ch R = 1 ,5018    ,498,498,498
BEGIN DESCRIPTION:
Sweetwater Creek Trib 8 9.0
END DESCRIPTION:
XS GIS Cut Line= 3
      1375405.03      6808138.04      1375593.51      6808436.51
      1375555.01      6808637.96
#Sta/Elev= 30
    4647 2394.69  4654.6 2394.78  4660.5 2392.53  4669.9 2391.56  4675.8  2389.2
  4718.2 2380.76  4741.6 2372.99  4768.4  2369.3  4930.8 2354.72    4937 2352.33
  4952.3 2350.72    4975 2341.85  4975.5 2341.35  4983.7 2341.85  4988.7 2342.48
  4997.9 2348.75  5003.3 2348.75  5011.7 2351.49  5017.7 2355.88  5022.8 2352.74
  5032.1 2355.23  5069.8 2359.61  5093.1 2355.51  5103.3 2354.95  5121.9 2365.21
    5127 2365.14  5164.4 2379.44  5179.1 2382.02  5184.8 2384.27  5205.1 2385.81
#Mann= 4 ,-1 , 0
    4647     .07       0  4768.4     .16       0    4975     .07       0
  4983.7     .16       0
Bank Sta=4975,4983.7
XS Rating Curve= 0 ,0
Exp/Cntr=0.3,0.1

Type RM Length L Ch R = 1 ,4520    ,499,499,499
BEGIN DESCRIPTION:
Sweetwater Creek Trib 8 8.0
END DESCRIPTION:
XS GIS Cut Line= 3
      1374754.97      6808137.97      1375145.32      6808548.78
        1375255.        6808738.
#Sta/Elev= 30
  4433.3  2469.2  4447.3 2466.18  4475.6 2456.45  4482.9 2451.37  4489.8 2449.05
  4511.2 2434.76  4518.1 2432.31  4539.5 2417.84    4582 2395.12  4610.3 2384.88
  4652.8 2375.57  4679.6 2371.69  4744.6  2366.4  4787.1 2358.56  4829.5 2354.02
    4978  2349.8  4992.1 2346.31  4996.1  2342.1  5002.4  2342.1  5002.7 2338.57
  5003.2 2338.07  5011.5 2338.57  5050.2 2343.65  5065.9 2349.22  5130.5 2356.88
    5152  2363.3  5167.8 2371.49  5189.3 2377.57  5195.6 2380.85  5218.7 2384.16
#Mann= 4 ,-1 , 0
  4433.3     .07       0  4679.6     .16       0  5002.7     .07       0
  5011.5     .16       0
Bank Sta=5002.7,5011.5
XS Rating Curve= 0 ,0
Exp/Cntr=0.3,0.1

Type RM Length L Ch R = 1 ,4021    ,499,499,499
BEGIN DESCRIPTION:
Sweetwater Creek Trib 8 7.0
END DESCRIPTION:
XS GIS Cut Line= 3
      1374505.01      6808438.01      1374753.41      6808834.17
      1375005.02        6808888.
#Sta/Elev= 30
  4532.4 2471.65  4555.4 2462.27  4574.7    2450  4640.2 2407.88  4649.6 2403.99
  4655.5  2398.9  4670.8 2392.75  4676.7 2388.13  4707.4 2374.31  4713.3 2370.22
  4734.5 2361.41  4756.6 2355.59  4801.6 2349.42  4910.1 2343.14  4945.5 2332.66
  4959.6 2332.94    4969 2328.71  4974.9 2330.31  4976.5 2327.76    4977 2327.26
  4985.4 2327.76  4996.1 2331.08  4999.3 2335.02  5026.1 2338.21  5052.8 2339.44
  5114.1 2346.95    5155 2348.46  5226.6 2364.85  5237.7 2371.47  5257.3  2376.6
#Mann= 5 ,-1 , 0
  4532.4     .07       0  4574.7     .16       0  4976.5     .07       0
  4985.4     .16       0  5026.1     .07       0
Bank Sta=4976.5,4985.4
XS Rating Curve= 0 ,0
Exp/Cntr=0.3,0.1

Type RM Length L Ch R = 1 ,3522    ,452,452,452
BEGIN DESCRIPTION:
Sweetwater Creek Trib 8 6.0
END DESCRIPTION:
XS GIS Cut Line= 3
        1374205.        6808738.      1374381.85      6809111.78
      1374504.99      6809387.97
#Sta/Elev= 30
  4586.5 2450.48  4589.3 2450.48  4595.1 2444.04  4600.6 2442.62  4617.9 2431.49
  4652.9  2413.9  4668.9 2409.71  4686.1 2402.33  4691.7 2398.17  4708.2 2393.29
  4737.2 2378.89  4771.9 2366.26  4833.7 2346.02  4863.1  2338.9    4902  2332.3
  4962.6 2328.64  4988.3 2320.81  4988.8 2320.31  4997.7 2320.81  5028.7 2329.14
  5039.4 2329.21  5050.6 2326.11  5061.6 2327.91  5073.6 2333.69  5137.8 2338.61
  5166.5 2348.63  5195.2 2348.73  5224.5 2355.85  5258.6 2366.35  5302.4 2382.73
#Mann= 5 ,-1 , 0
  4586.5     .07       0  4771.9     .16       0  4988.3     .07       0
  4997.7     .16       0  5224.5     .07       0
Bank Sta=4988.3,4997.7
XS Rating Curve= 0 ,0
Exp/Cntr=0.3,0.1

Type RM Length L Ch R = 1 ,3070    ,483,483,483
BEGIN DESCRIPTION:
Sweetwater Creek Trib 8 5.0
END DESCRIPTION:
XS GIS Cut Line= 3
      1373754.98      6808837.96      1373970.39      6809238.97
        1373955.      6809337.98
#Sta/Elev= 30
  4544.8  2401.4  4547.7  2401.4    4553 2394.81  4558.6 2393.08  4574.9 2382.72
    4613 2367.06  4618.7 2362.23  4624.4 2361.73    4635 2355.49  4640.6 2355.51
    4647 2350.27  4656.9 2345.84  4678.8  2342.4  4684.5 2344.34  4722.6 2338.08
  4728.3  2338.9  4744.5 2334.49  4885.4 2328.78  4964.8 2327.84    4980 2325.46
  4994.9 2316.86  4995.4 2316.36  5004.3 2316.86  5015.7 2317.93  5059.7 2325.33
  5066.2  2330.3  5071.3 2330.65  5090.1 2345.27  5097.7 2353.39  5100.2 2353.39
#Mann= 4 ,-1 , 0
  4544.8     .16       0  4994.9     .07       0  5004.3     .16       0
  5015.7     .07       0
Bank Sta=4994.9,5004.3
XS Rating Curve= 0 ,0
Exp/Cntr=0.3,0.1

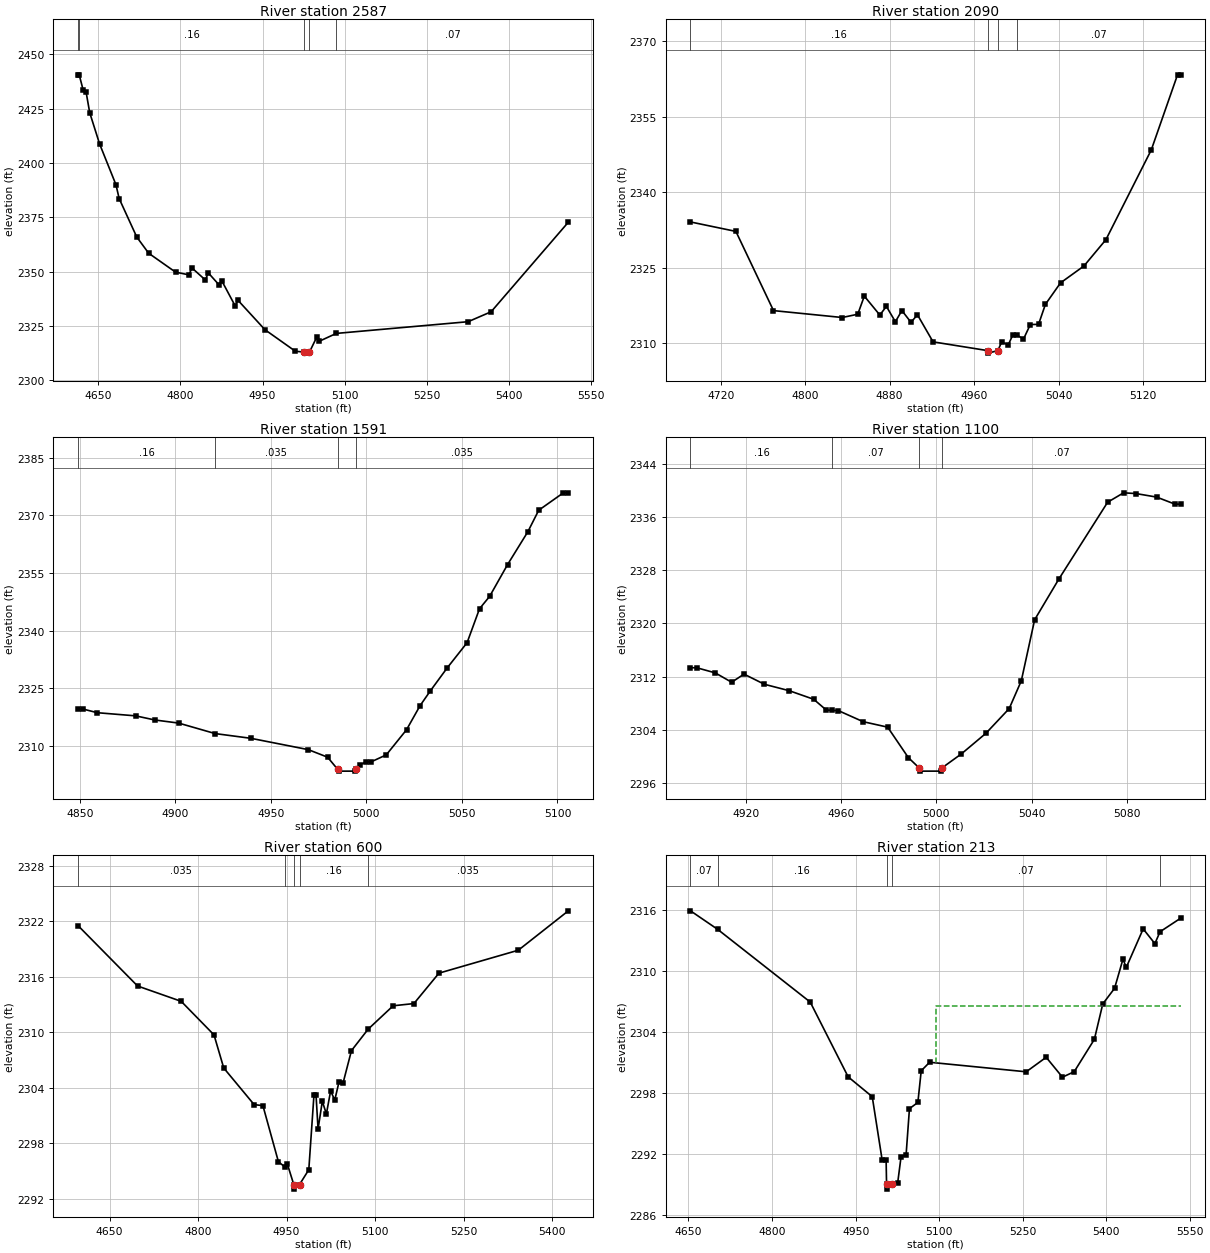
Type RM Length L Ch R = 1 ,2587    ,497,497,497
BEGIN DESCRIPTION:
Sweetwater Creek Trib 8 4.0
END DESCRIPTION:
XS GIS Cut Line= 3
      1373705.02      6808787.95      1373564.58      6809148.47
      1373720.29      6809632.12
#Sta/Elev= 30
  4613.1 2440.61  4615.4 2440.61  4622.7 2433.56  4628.1 2432.52  4634.6 2423.17
  4652.6 2408.81  4682.5    2390  4688.3 2383.65  4720.5 2365.91  4742.2 2358.46
  4791.2 2349.76  4815.7  2348.5  4821.1 2351.71  4845.6 2346.15    4851 2349.42
  4870.1 2344.04  4875.5 2345.83    4900 2334.23  4905.3 2336.76  4954.4 2323.25
    5010 2313.31  5026.3 2312.96  5026.8 2312.46  5035.7 2312.96  5048.6 2319.66
  5053.8 2317.96  5084.7 2321.54  5325.2 2326.93  5367.2 2331.51  5508.1 2372.75
#Mann= 5 ,-1 , 0
  4613.1     .07       0  4615.4     .16       0  5026.3     .07       0
  5035.7     .16       0  5084.7     .07       0
Bank Sta=5026.3,5035.7
XS Rating Curve= 0 ,0
Exp/Cntr=0.3,0.1

Type RM Length L Ch R = 1 ,2090    ,499,499,499
BEGIN DESCRIPTION:
Sweetwater Creek Trib 8 3.0
END DESCRIPTION:
XS GIS Cut Line= 3
      1373304.97      6809337.98      1373555.68      6809517.93
      1373654.98      6809637.98
#Sta/Elev= 30
  4691.4  2334.1  4734.4 2332.22    4770 2316.48  4835.1 2315.11  4849.8 2315.76
    4856 2319.36  4870.7  2315.6  4876.9 2317.32  4885.4 2314.27  4891.6 2316.49
  4900.2 2314.15  4906.3 2315.66  4921.1 2310.27  4972.8 2308.53  4973.3 2308.03
  4982.4 2308.53  4986.1 2310.23  4992.3 2309.68  4996.5 2311.58    5001 2311.58
  5006.7  2310.8  5013.2 2313.71    5021 2313.75  5027.5 2317.73  5041.8 2321.99
    5064 2325.35  5084.8 2330.58  5127.8 2348.44  5152.6 2363.34  5155.8 2363.34
#Mann= 4 ,-1 , 0
  4691.4     .16       0  4972.8     .07       0  4982.4     .16       0
    5001     .07       0
Bank Sta=4972.8,4982.4
XS Rating Curve= 0 ,0
Exp/Cntr=0.3,0.1

Type RM Length L Ch R = 1 ,1591    ,491,491,491
BEGIN DESCRIPTION:
Sweetwater Creek Trib 8 2.0
END DESCRIPTION:
XS GIS Cut Line= 3
        1373205.      6809687.97      1373220.09      6809838.21
      1373254.99      6809937.98
#Sta/Elev= 30
    4849 2319.59  4851.5 2319.59  4859.1 2318.62  4879.2  2317.8  4889.2 2316.73
  4901.7 2315.92  4920.8 2313.19  4939.5 2311.96  4969.6 2309.01  4979.7 2307.04
  4984.9 2303.92  4985.4 2303.42  4994.1 2303.42  4994.6 2303.92  4996.9 2305.06
  4999.6 2305.84  5002.5 2305.84  5010.4 2307.65    5021 2314.18  5028.1 2320.46
  5033.4 2324.25  5042.2 2330.22  5052.7 2336.83  5059.2 2345.66  5064.5 2348.88
  5073.9 2357.16  5084.5 2365.69  5090.2 2371.29  5103.1 2375.82  5105.7 2375.82
#Mann= 4 ,-1 , 0
    4849     .16       0  4920.8    .035       0  4984.9    .035       0
  4994.6    .035       0
Bank Sta=4984.9,4994.6
XS Rating Curve= 0 ,0
Exp/Cntr=0.3,0.1

Type RM Length L Ch R = 1 ,1100    ,500,500,500
BEGIN DESCRIPTION:
Sweetwater Creek Trib 8 1.0
END DESCRIPTION:
XS GIS Cut Line= 3
        1372805.      6809787.99      1372777.84      6809887.75
        1372755.      6809987.98
#Sta/Elev= 30
  4896.6 2313.35  4899.2 2313.35    4907 2312.58  4913.9 2311.17  4919.1 2312.39
  4927.7 2310.86  4938.1  2309.9  4948.4 2308.61  4953.7 2306.99  4956.3 2306.94
  4958.8  2306.9  4969.2 2305.24  4979.5 2304.42  4988.2 2299.84  4992.7 2298.31
  4993.2 2297.81  5001.9 2297.81  5002.4 2298.31  5010.5  2300.4  5020.8 2303.49
  5030.6 2307.21  5035.7 2311.39  5041.3 2320.56  5051.5 2326.69    5072 2338.23
  5078.7 2339.64  5083.9 2339.53  5092.6    2339  5100.3 2337.94  5102.8 2337.94
#Mann= 4 ,-1 , 0
  4896.6     .16       0  4956.3     .07       0  4992.7     .07       0
  5002.4     .07       0
Bank Sta=4992.7,5002.4
XS Rating Curve= 0 ,0
Exp/Cntr=0.3,0.1

Type RM Length L Ch R = 1 ,600     ,387,387,387
BEGIN DESCRIPTION:
Sweetwater Creek Trib 8 1192
END DESCRIPTION:
XS GIS Cut Line= 3
        1372405.        6809488.      1372308.29      6809879.94
      1372604.99      6810187.99
#Sta/Elev= 30
  4596.3 2321.54  4697.4    2315  4771.4 2313.34    4827 2309.71  4843.5 2306.13
    4895 2302.17  4909.9 2302.06  4936.2 2295.99  4946.5 2295.46  4951.4 2295.73
  4962.2 2293.53  4962.7 2293.03    4972 2293.53  4987.7 2295.13  4996.4 2303.17
    5000 2303.17  5003.4 2299.52  5010.6 2302.53  5017.5 2301.16  5024.7 2303.65
  5031.7 2302.66  5038.9 2304.62  5045.8 2304.51    5060 2308.01  5088.3 2310.33
  5130.7 2312.86  5165.9  2313.1  5208.4 2316.39  5342.9 2318.87  5427.7 2323.13
#Mann= 5 ,-1 , 0
  4596.3    .035       0  4946.5     .16       0  4962.2     .07       0
    4972     .16       0  5088.3    .035       0
Bank Sta=4962.2,4972
XS Rating Curve= 0 ,0
Exp/Cntr=0.3,0.1

Type RM Length L Ch R = 1 ,213     ,0,0,0
BEGIN DESCRIPTION:
Sweetwater Creek Trib 8 4403
END DESCRIPTION:
XS GIS Cut Line= 3
      1372004.75      6809445.79      1371950.41       6809787.9
      1372397.54      6810079.49
#Sta/Elev= 30
  4653.6 2315.93  4702.2 2314.11  4868.5 2306.94  4936.6 2299.57  4979.8 2297.62
  4997.5 2291.41  5004.7 2291.41  5005.5 2289.01    5006 2288.51  5015.3 2289.01
  5025.5 2289.14  5031.5 2291.69  5040.6 2291.92  5046.6 2296.44  5061.7 2297.05
  5067.7 2300.17  5082.8 2301.01  5256.2 2300.07    5292  2301.5  5321.2 2299.54
  5342.3 2300.08  5378.5 2303.27  5393.6 2306.76  5414.7 2308.29  5429.8 2311.16
  5435.8 2310.36  5466.1 2314.15  5487.1  2312.7  5496.4 2313.87  5533.8 2315.22
#Mann= 5 ,-1 , 0
  4653.6     .07       0  4702.2     .16       0  5005.5     .07       0
  5015.3     .07       0  5496.4     .07       0
#XS Ineff= 2 , 0
                          5093.4         2306.53
Permanent Ineff=
       F       F
Bank Sta=5005.5,5015.3
XS Rating Curve= 0 ,0
Exp/Cntr=0.3,0.1

Chan Stop Cuts=-1
Use User Specified Reach Order=0
Composite Channel Slope=5