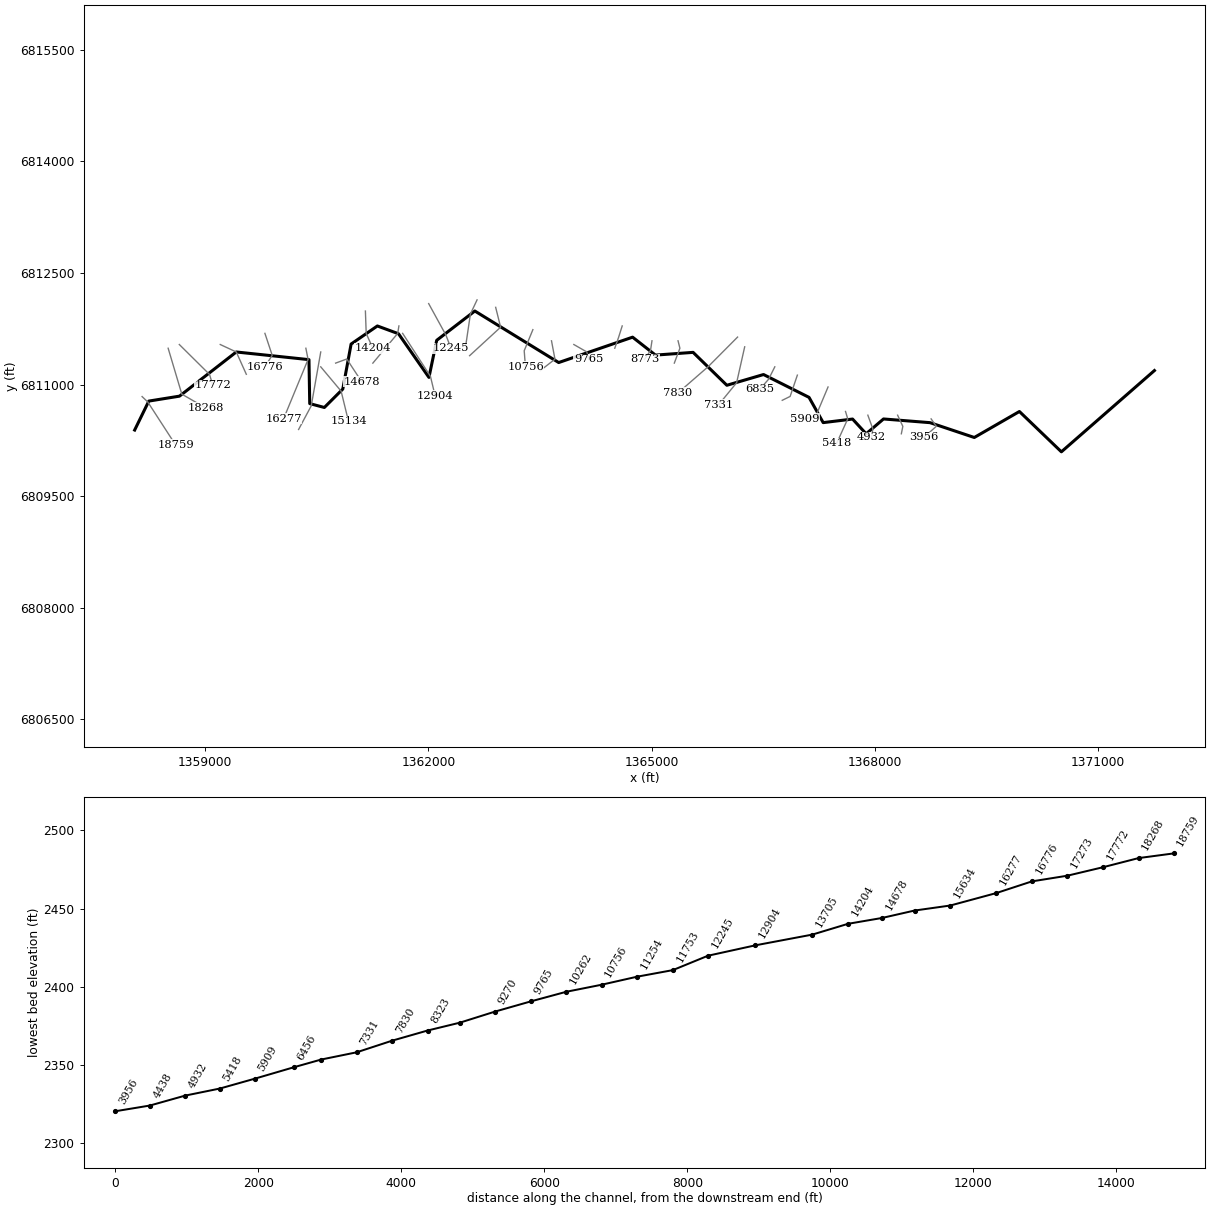
--- Sweetwater Creek Trib 9.prj (project) ---

Proj Title=Sweetwater Creek Trib 9 Base Level Engineering
Current Plan=p01
Default Exp/Contr=0.3,0.1
English Units
Geom File=g01
Flow File=f01
Plan File=p01
Y Axis Title=Elevation
X Axis Title(PF)=Main Channel Distance
X Axis Title(XS)=Station
BEGIN DESCRIPTION:
Sweetwater Creek Trib 9
END DESCRIPTION:
DSS Export Rating Curves= 0
DSS Export Rating Curve Sorted= 0
DSS Export Volume Flow Curves= 0
DXF OffsetX= 0
DXF OffsetY= 0
DXF ScaleX= 1
DXF ScaleY= 10

--- Sweetwater Creek Trib 9.p01 (plan) ---

Plan Title=Multiple Run
Short Identifier=Multiple
Geom File=g01
Flow File=f01
Subcritical Flow
K Sum by GR= 0
Std Step Tol= 0.01
Critical Tol= 0.01
Num of Std Step Trials= 20
Max Error Tol= 0.3
Flow Tol Ratio= 0.001
Split Flow NTrial= 30
Split Flow Tol= 0.02
Split Flow Ratio= 0.02
Log Output Level= 0
Friction Slope Method= 1
Unsteady Friction Slope Method= 2
Unsteady Bridges Friction Slope Method= 1
Parabolic Critical Depth
Global Vel Dist=  1 , 1 , 1
Global Log Level= 0
CheckData=True
Encroach Param= -1, 0, 0, 0
BEGIN DESCRIPTION:
Multiple Run
END DESCRIPTION:

--- Sweetwater Creek Trib 9.f01 (steady flow) ---

Flow Title=Multiple
Number of Profiles=7
Profile Names=10-year,25-year,50-year,1pct_min,100-year,1pct_plu,500-year
River Rch & RM= Sweetwater Creek,Reach-1,18759
     305     438     551     345     688    1373    1087
River Rch & RM= Sweetwater Creek,Reach-1,17772
     447     653     831     526    1049    2093    1694
River Rch & RM= Sweetwater Creek,Reach-1,7830
     482     707     902     572    1141    2276    1850
River Rch & RM= Sweetwater Creek,Reach-1,5418
     706    1055    1364     875    1746    3484    2900
Boundary for River Rch & Prof#=Sweetwater Creek,Reach-1,1
Up Type=0
Dn Type=3
Dn Slope=0.005
Boundary for River Rch & Prof#=Sweetwater Creek,Reach-1,2
Up Type=0
Dn Type=3
Dn Slope=0.005
Boundary for River Rch & Prof#=Sweetwater Creek,Reach-1,3
Up Type=0
Dn Type=3
Dn Slope=0.005
Boundary for River Rch & Prof#=Sweetwater Creek,Reach-1,4
Up Type=0
Dn Type=3
Dn Slope=0.005
Boundary for River Rch & Prof#=Sweetwater Creek,Reach-1,5
Up Type=0
Dn Type=3
Dn Slope=0.005
Boundary for River Rch & Prof#=Sweetwater Creek,Reach-1,6
Up Type=0
Dn Type=3
Dn Slope=0.005
Boundary for River Rch & Prof#=Sweetwater Creek,Reach-1,7
Up Type=0
Dn Type=3
Dn Slope=0.005

--- Sweetwater Creek Trib 9.g01 (geometry) ---

Geom Title=Existing Conditions

River Reach=Sweetwater Creek,Reach-1
Reach XY= 30
      1358055.00      6810388.00      1358245.18      6810777.53
      1358657.31      6810843.82      1359420.16      6811437.61
      1360396.91      6811334.65      1360406.97      6810743.65
      1360603.53      6810691.53      1360851.39      6810939.50
      1360962.85      6811544.19      1361315.64      6811787.44
      1361599.59      6811682.82      1362008.62      6811095.47
      1362112.69      6811594.48      1362625.06      6811988.51
      1363751.66      6811295.60      1364744.50      6811636.80
      1365051.58      6811395.79      1365557.42      6811432.46
      1366010.89      6810989.96      1366503.54      6811134.47
      1367114.83      6810827.53      1367305.00      6810488.00
      1367699.76      6810535.92      1367882.22      6810337.51
      1368115.48      6810537.07      1368739.79      6810487.49
      1369334.97      6810288.07      1369941.05      6810637.48
      1370505.10      6810095.32      1371755.00      6811188.00

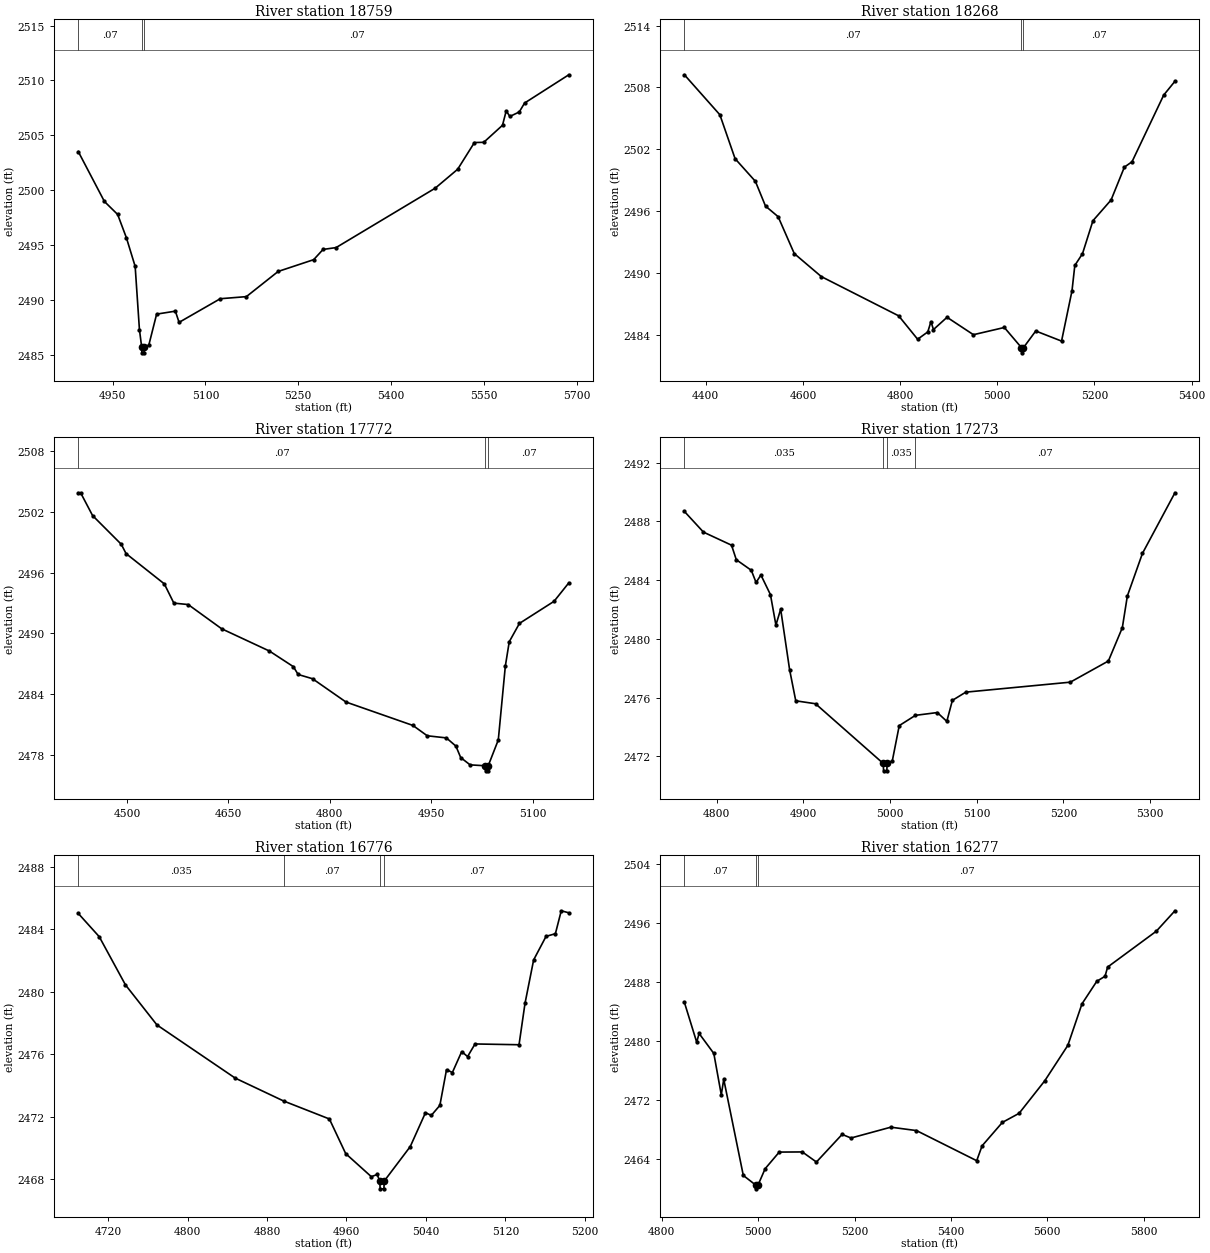
Type RM Length L Ch R = 1,18759,491,491,491
BEGIN DESCRIPTION:
Sweetwater Creek Trib 9 36.0
END DESCRIPTION:
XS GIS Cut Line= 3
      1358154.98      6810838.02      1358231.42      6810765.16
      1358604.99      6810188.01
#Sta/Elev= 30
  4894.4 2503.54  4936.7 2499.00  4958.1 2497.82  4972.3 2495.69  4986.4 2493.10
  4993.3 2487.36  4997.0 2485.74  4997.3 2485.24  5000.8 2485.24  5001.0 2485.74
  5008.5 2485.95  5021.1 2488.76  5051.4 2489.03  5057.4 2488.01  5124.0 2490.16
  5166.2 2490.35  5217.6 2492.64  5275.0 2493.71  5290.2 2494.64  5311.3 2494.81
  5471.5 2500.21  5507.8 2501.93  5534.9 2504.36  5550.0 2504.38  5580.3 2505.93
  5586.3 2507.24  5592.2 2506.73  5607.4 2507.14  5616.0 2507.95  5687.5 2510.52
#Mann=3,-1,0
  4894.4    0.07       0  4997.0    0.07       0  5001.0    0.07       0
Bank Sta=4997,5001
Exp/Cntr=0.3,0.1

Type RM Length L Ch R = 1,18268,496,496,496
BEGIN DESCRIPTION:
Sweetwater Creek Trib 9 35.0
END DESCRIPTION:
XS GIS Cut Line= 3
      1358505.00      6811487.99      1358688.58      6810870.92
      1359005.01      6810687.99
#Sta/Elev= 30
  4356.2 2509.23  4429.2 2505.35  4460.5 2501.09  4502.3 2498.89  4523.1 2496.49
  4549.1 2495.46  4582.3 2491.88  4637.9 2489.65  4797.1 2485.84  4836.1 2483.57
  4857.0 2484.28  4863.5 2485.28  4868.7 2484.51  4896.6 2485.70  4950.9 2484.01
  5014.5 2484.71  5049.8 2482.75  5050.1 2482.25  5053.8 2482.75  5079.1 2484.37
  5132.2 2483.39  5153.7 2488.27  5159.5 2490.73  5175.3 2491.87  5196.8 2495.07
  5234.1 2497.08  5261.5 2500.27  5277.2 2500.79  5342.4 2507.26  5365.5 2508.60
#Mann=3,-1,0
  4356.2    0.07       0  5049.8    0.07       0  5053.8    0.07       0
Bank Sta=5049.8,5053.8
Exp/Cntr=0.3,0.1

Type RM Length L Ch R = 1,17772,499,499,499
BEGIN DESCRIPTION:
Sweetwater Creek Trib 9 34.0
END DESCRIPTION:
XS GIS Cut Line= 3
      1358655.00      6811538.00      1359061.17      6811135.25
      1359104.99      6810988.03
#Sta/Elev= 30
  4428.0 2503.87  4431.5 2503.87  4449.2 2501.62  4491.6 2498.79  4498.7 2497.87
  4555.3 2494.88  4569.4 2492.98  4590.6 2492.84  4640.1 2490.45  4710.8 2488.25
  4746.2 2486.71  4753.2 2485.94  4774.5 2485.52  4824.0 2483.22  4923.0 2480.91
  4944.2 2479.89  4972.5 2479.68  4986.6 2478.87  4993.7 2477.74  5007.6 2477.02
  5030.1 2476.93  5030.4 2476.43  5034.1 2476.43  5034.4 2476.93  5049.3 2479.48
  5059.7 2486.76  5065.5 2489.17  5080.6 2490.98  5131.8 2493.16  5153.6 2494.98
#Mann=3,-1,0
  4428.0    0.07       0  5030.1    0.07       0  5034.4    0.07       0
Bank Sta=5030.1,5034.4
Exp/Cntr=0.3,0.1

Type RM Length L Ch R = 1,17273,497,497,497
BEGIN DESCRIPTION:
Sweetwater Creek Trib 9 33.0
END DESCRIPTION:
XS GIS Cut Line= 3
      1359205.02      6811537.99      1359420.16      6811437.61
      1359555.02      6811137.96
#Sta/Elev= 30
  4762.6 2488.68  4784.6 2487.27  4817.0 2486.38  4822.5 2485.39  4839.8 2484.67
  4845.3 2483.84  4850.9 2484.35  4861.9 2483.01  4868.2 2480.94  4873.7 2482.02
  4884.0 2477.90  4891.1 2475.78  4913.9 2475.58  4992.1 2471.51  4992.4 2471.01
  4996.2 2471.01  4996.5 2471.51  5002.5 2471.69  5010.5 2474.09  5029.2 2474.79
  5054.4 2474.98  5065.4 2474.38  5071.8 2475.81  5087.3 2476.37  5207.9 2477.05
  5251.8 2478.49  5267.9 2480.76  5273.7 2482.92  5291.1 2485.82  5328.6 2489.95
#Mann=4,-1,0
  4762.6   0.035       0  4992.1   0.035       0  4996.5   0.035       0
  5029.2    0.07       0
Bank Sta=4992.1,4996.5
Exp/Cntr=0.3,0.1

Type RM Length L Ch R = 1,16776,499,499,499
BEGIN DESCRIPTION:
Sweetwater Creek Trib 9 32.0
END DESCRIPTION:
XS GIS Cut Line= 3
      1359805.01      6811687.96      1359902.67      6811393.75
      1359805.02      6811238.03
#Sta/Elev= 30
  4690.0 2485.03  4711.1 2483.54  4737.5 2480.45  4769.2 2477.88  4848.0 2474.47
  4896.8 2473.00  4942.8 2471.85  4959.2 2469.63  4985.0 2468.15  4990.9 2468.29
  4993.5 2467.87  4993.9 2467.37  4997.7 2467.37  4998.0 2467.87  5024.2 2470.08
  5039.5 2472.25  5045.4 2472.08  5054.0 2472.72  5060.7 2475.01  5066.6 2474.83
  5076.0 2476.17  5081.9 2475.85  5089.4 2476.66  5133.7 2476.61  5139.7 2479.26
  5148.4 2482.05  5160.9 2483.56  5170.3 2483.73  5176.2 2485.20  5183.8 2485.07
#Mann=4,-1,0
  4690.0   0.035       0  4896.8    0.07       0  4993.5    0.07       0
  4998.0    0.07       0
Bank Sta=4993.5,4998
Exp/Cntr=0.3,0.1

Type RM Length L Ch R = 1,16277,643,643,643
BEGIN DESCRIPTION:
Sweetwater Creek Trib 9 31.0
END DESCRIPTION:
XS GIS Cut Line= 3
      1360355.01      6811487.96      1360384.91      6811337.70
      1360054.99      6810537.98
#Sta/Elev= 30
  4846.8 2485.21  4872.3 2479.81  4877.4 2480.98  4907.9 2478.27  4923.4 2472.66
  4928.5 2474.76  4969.1 2461.71  4995.1 2460.39  4995.4 2459.89  4999.6 2460.39
  5014.4 2462.62  5043.7 2464.88  5091.6 2464.90  5120.9 2463.53  5174.2 2467.28
  5192.7 2466.79  5275.3 2468.26  5328.6 2467.80  5453.6 2463.71  5464.8 2465.73
  5506.9 2468.91  5541.6 2470.14  5594.9 2474.56  5642.8 2479.37  5672.1 2485.00
  5702.8 2488.06  5720.0 2488.75  5725.4 2490.00  5826.5 2494.87  5865.1 2497.64
#Mann=3,-1,0
  4846.8    0.07       0  4995.1    0.07       0  4999.6    0.07       0
Bank Sta=4995.1,4999.6
Exp/Cntr=0.3,0.1

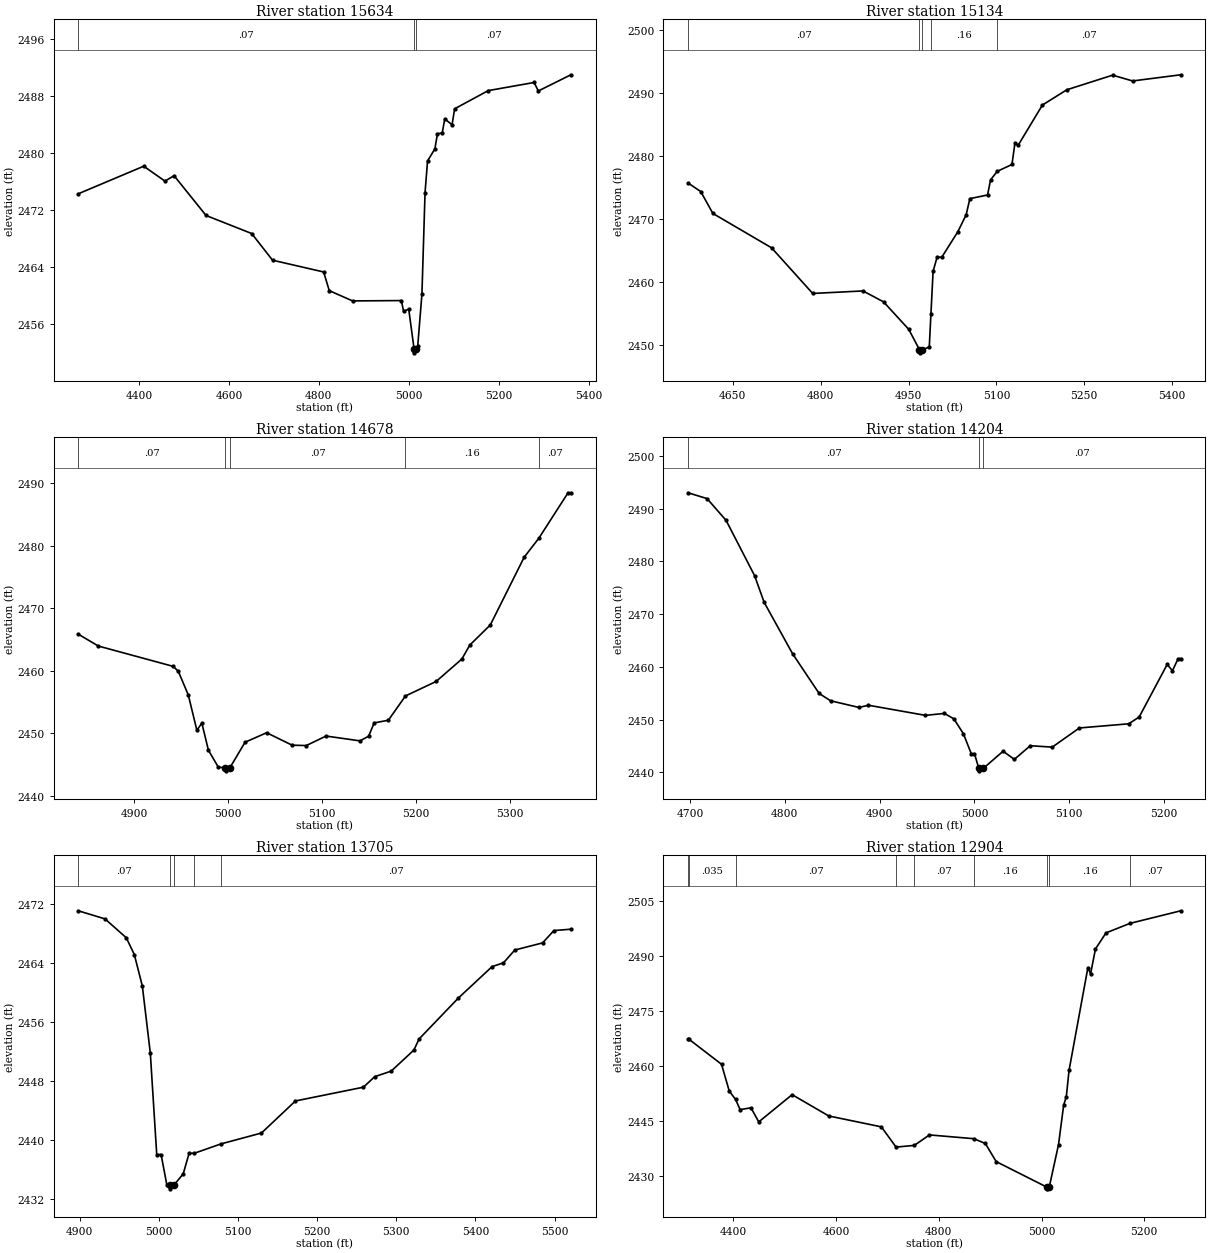
Type RM Length L Ch R = 1,15634,500,500,500
BEGIN DESCRIPTION:
Sweetwater Creek Trib 9 30.0
END DESCRIPTION:
XS GIS Cut Line= 3
      1360554.99      6811437.95      1360427.65      6810713.97
      1360257.57      6810395.89
#Sta/Elev= 30
  4264.9 2474.25  4410.6 2478.12  4457.8 2476.03  4478.1 2476.79  4549.2 2471.21
  4650.7 2468.68  4697.1 2464.94  4810.7 2463.29  4823.3 2460.67  4875.1 2459.23
  4983.6 2459.28  4988.6 2457.77  5000.0 2458.08  5012.0 2452.45  5012.3 2451.95
  5016.7 2452.45  5020.0 2452.87  5029.4 2460.22  5036.3 2474.42  5041.9 2478.86
  5058.2 2480.56  5063.9 2482.67  5074.5 2482.78  5080.2 2484.76  5096.4 2483.92
  5102.1 2486.17  5176.9 2488.72  5278.9 2489.86  5288.3 2488.67  5360.7 2490.94
#Mann=3,-1,0
  4264.9    0.07       0  5012.0    0.07       0  5016.7    0.07       0
Bank Sta=5012,5016.7
Exp/Cntr=0.3,0.1

Type RM Length L Ch R = 1,15134,456,456,456
BEGIN DESCRIPTION:
Sweetwater Creek Trib 9 29.0
END DESCRIPTION:
XS GIS Cut Line= 3
      1360555.00      6811238.00      1360828.82      6810911.13
      1360927.10      6810508.04
#Sta/Elev= 30
  4573.6 2475.67  4595.1 2474.33  4615.9 2470.85  4716.1 2465.40  4786.3 2458.16
  4872.2 2458.56  4907.3 2456.83  4950.3 2452.47  4968.7 2449.24  4969.0 2448.74
  4973.5 2449.24  4985.4 2449.66  4988.2 2454.83  4991.9 2461.66  4998.8 2463.94
  5006.7 2463.90  5034.1 2467.94  5048.4 2470.64  5054.7 2473.20  5084.9 2473.78
  5090.1 2476.18  5101.4 2477.53  5126.6 2478.62  5131.8 2482.08  5137.0 2481.64
  5178.6 2488.05  5220.3 2490.47  5298.5 2492.79  5332.6 2491.87  5414.9 2492.85
#Mann=5,-1,0
  4573.6    0.07       0  4968.7    0.07       0  4973.5    0.07       0
  4988.2    0.16       0  5101.4    0.07       0
Bank Sta=4968.7,4973.5
Exp/Cntr=0.3,0.1

Type RM Length L Ch R = 1,14678,474,474,474
BEGIN DESCRIPTION:
Sweetwater Creek Trib 9 28.0
END DESCRIPTION:
XS GIS Cut Line= 3
      1360755.02      6811288.01      1360904.56      6811343.18
      1361104.99      6811038.02
#Sta/Elev= 30
  4840.6 2465.84  4861.9 2463.94  4941.8 2460.68  4947.2 2459.88  4957.8 2456.11
  4966.9 2450.47  4972.2 2451.62  4979.2 2447.28  4989.8 2444.56  4997.3 2444.49
  4997.7 2443.99  5002.1 2444.49  5018.2 2448.56  5041.2 2450.08  5068.3 2448.09
  5083.4 2448.03  5104.4 2449.55  5140.6 2448.78  5149.7 2449.52  5155.7 2451.65
  5170.8 2452.08  5189.0 2455.96  5221.6 2458.27  5249.1 2461.87  5257.4 2464.08
  5279.3 2467.30  5315.4 2478.14  5331.0 2481.17  5362.1 2488.43  5365.1 2488.43
#Mann=5,-1,0
  4840.6    0.07       0  4997.3    0.07       0  5002.1    0.07       0
  5189.0    0.16       0  5331.0    0.07       0
Bank Sta=4997.3,5002.1
Exp/Cntr=0.3,0.1

Type RM Length L Ch R = 1,14204,499,499,499
BEGIN DESCRIPTION:
Sweetwater Creek Trib 9 27.0
END DESCRIPTION:
XS GIS Cut Line= 3
      1361155.00      6811988.01      1361165.70      6811686.30
      1361255.01      6811487.98
#Sta/Elev= 30
  4698.1 2493.00  4718.1 2491.89  4738.1 2487.77  4768.2 2477.27  4778.2 2472.24
  4808.2 2462.48  4836.2 2454.95  4848.2 2453.56  4878.2 2452.29  4888.2 2452.71
  4948.3 2450.79  4968.3 2451.16  4978.3 2450.12  4988.3 2447.31  4996.6 2443.52
  5000.0 2443.52  5004.5 2440.77  5004.9 2440.27  5009.5 2440.77  5030.2 2443.99
  5042.0 2442.44  5058.8 2445.03  5082.0 2444.77  5110.6 2448.40  5162.6 2449.19
  5173.6 2450.47  5203.2 2460.46  5208.7 2459.24  5214.7 2461.55  5217.5 2461.55
#Mann=3,-1,0
  4698.1    0.07       0  5004.5    0.07       0  5009.5    0.07       0
Bank Sta=5004.5,5009.5
Exp/Cntr=0.3,0.1

Type RM Length L Ch R = 1,13705,801,801,801
BEGIN DESCRIPTION:
Sweetwater Creek Trib 9 26.0
END DESCRIPTION:
XS GIS Cut Line= 3
      1361605.00      6811787.99      1361589.17      6811687.33
      1361255.00      6811288.00
#Sta/Elev= 30
  4898.1 2471.13  4931.9 2470.03  4958.8 2467.47  4969.0 2465.18  4979.1 2460.92
  4989.2 2451.80  4997.3 2438.04  5002.8 2438.04  5010.0 2433.96  5014.0 2433.88
  5014.3 2433.38  5019.0 2433.88  5030.8 2435.42  5038.2 2438.21  5044.8 2438.21
  5078.5 2439.48  5129.7 2440.96  5172.6 2445.31  5258.5 2447.18  5272.8 2448.61
  5293.6 2449.36  5322.3 2452.22  5328.8 2453.72  5378.2 2459.25  5421.2 2463.56
  5435.5 2464.06  5449.8 2465.80  5484.9 2466.77  5499.2 2468.44  5520.7 2468.63
#Mann=5,-1,0
  4898.1    0.07       0  5014.0    0.07       0  5019.0    0.07       0
  5044.8   0.035       0  5078.5    0.07       0
Bank Sta=5014,5019
Exp/Cntr=0.3,0.1

Type RM Length L Ch R = 1,12904,659,659,659
BEGIN DESCRIPTION:
Sweetwater Creek Trib 9 25.0
END DESCRIPTION:
XS GIS Cut Line= 3
      1361655.01      6811687.99      1362028.83      6811110.18
      1362091.89      6810846.41
#Sta/Elev= 30
  4311.8 2467.25  4313.9 2467.25  4376.8 2460.48  4391.9 2453.16  4404.2 2450.88
  4413.0 2448.10  4434.2 2448.60  4449.3 2444.75  4514.3 2452.18  4585.7 2446.37
  4688.1 2443.40  4716.7 2437.88  4752.3 2438.34  4781.7 2441.20  4868.3 2440.17
  4890.6 2438.86  4911.7 2433.92  5009.9 2426.99  5010.3 2426.49  5015.1 2426.99
  5033.1 2438.56  5043.1 2449.30  5048.3 2451.65  5053.6 2458.80  5090.3 2486.84
  5095.5 2485.15  5105.1 2491.95  5125.6 2496.32  5172.2 2498.91  5271.2 2502.35
#Mann=9,-1,0
  4311.8    0.07       0  4313.9   0.035       0  4404.2    0.07       0
  4716.7   0.035       0  4752.3    0.07       0  4868.3    0.16       0
  5009.9    0.07       0  5015.1    0.16       0  5172.2    0.07       0
Bank Sta=5009.9,5015.1
Exp/Cntr=0.3,0.1

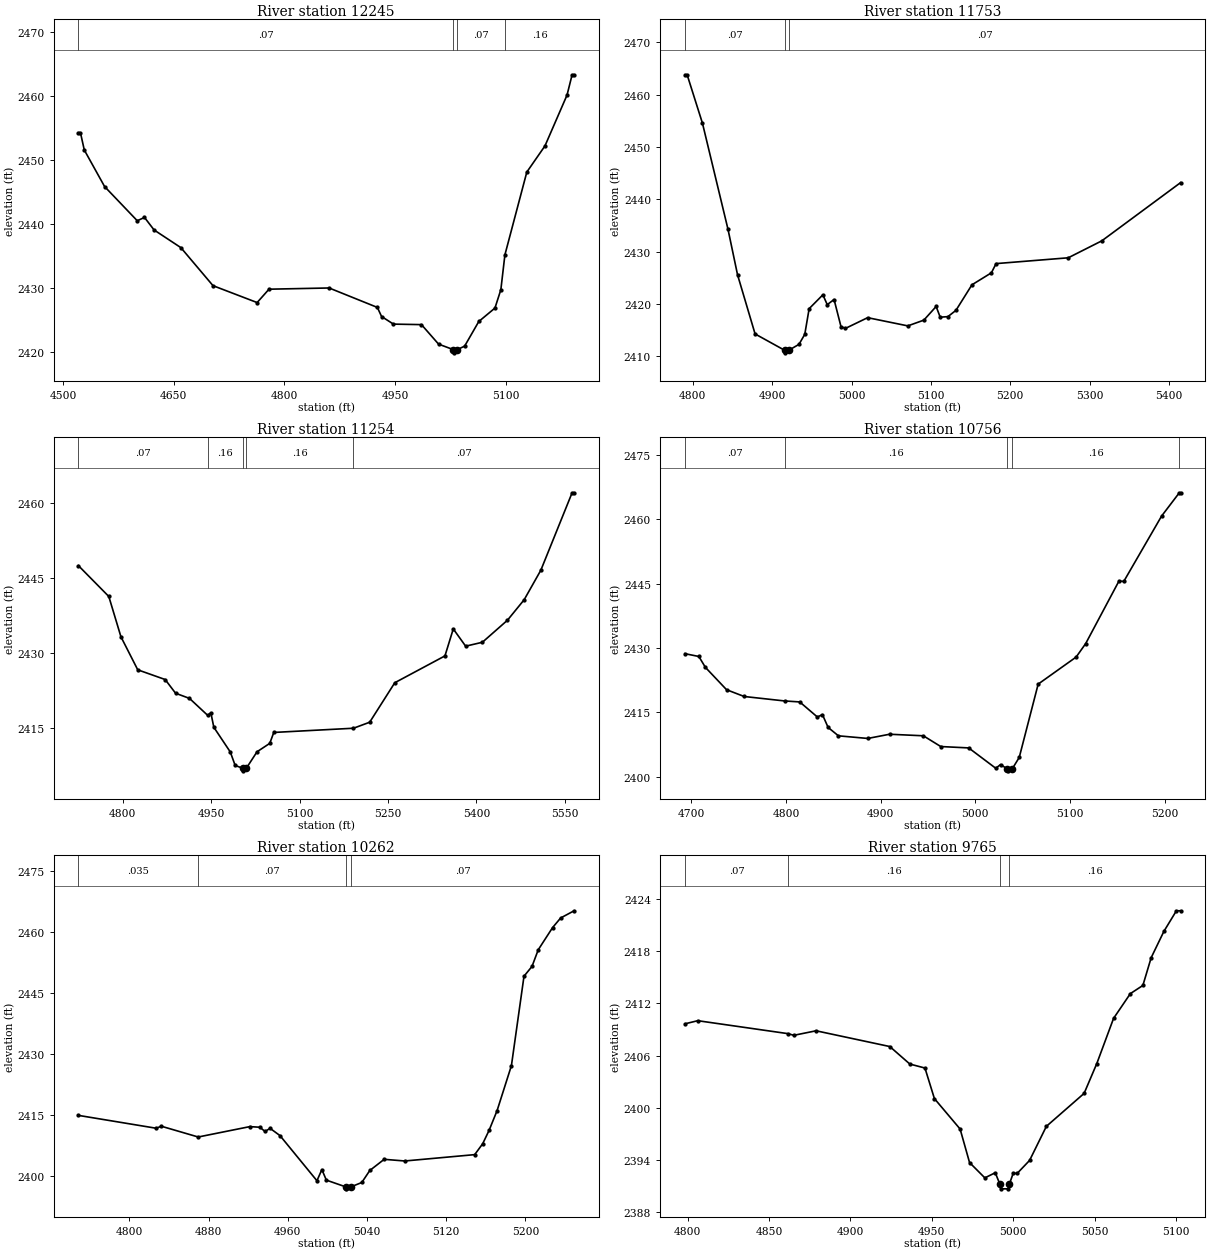
Type RM Length L Ch R = 1,12245,492,492,492
BEGIN DESCRIPTION:
Sweetwater Creek Trib 9 24.0
END DESCRIPTION:
XS GIS Cut Line= 3
      1362005.01      6812087.98      1362235.23      6811667.59
      1362305.01      6811487.97
#Sta/Elev= 30
  4520.7 2454.29  4523.5 2454.29  4528.7 2451.59  4556.2 2445.88  4600.5 2440.53
  4610.3 2441.05  4623.3 2439.09  4659.6 2436.33  4703.2 2430.38  4763.0 2427.74
  4779.1 2429.83  4860.6 2430.02  4926.0 2426.98  4931.7 2425.56  4947.8 2424.37
  4985.8 2424.29  5009.0 2421.24  5029.1 2420.38  5029.5 2419.88  5034.3 2420.38
  5044.3 2420.93  5063.5 2424.78  5085.4 2426.88  5093.4 2429.75  5098.9 2435.20
  5128.6 2448.14  5153.2 2452.23  5183.1 2460.17  5190.0 2463.35  5192.7 2463.35
#Mann=4,-1,0
  4520.7    0.07       0  5029.1    0.07       0  5034.3    0.07       0
  5098.9    0.16       0
Bank Sta=5029.1,5034.3
Exp/Cntr=0.3,0.1

Type RM Length L Ch R = 1,11753,499,499,499
BEGIN DESCRIPTION:
Sweetwater Creek Trib 9 23.0
END DESCRIPTION:
XS GIS Cut Line= 3
      1362655.01      6812138.03      1362565.65      6811948.10
      1362504.99      6811537.96
#Sta/Elev= 30
  4790.1 2463.81  4792.9 2463.81  4812.2 2454.55  4844.4 2434.27  4856.4 2425.59
  4878.5 2414.29  4915.6 2411.18  4916.0 2410.68  4921.0 2411.18  4933.8 2412.30
  4941.1 2414.22  4946.6 2419.12  4963.9 2421.77  4969.4 2419.89  4978.0 2420.87
  4986.7 2415.70  4992.2 2415.34  5020.3 2417.40  5070.9 2415.83  5091.1 2416.93
  5106.6 2419.54  5111.7 2417.49  5121.4 2417.60  5131.5 2418.79  5151.7 2423.68
  5176.2 2425.97  5182.1 2427.73  5273.0 2428.84  5315.3 2432.08  5414.6 2443.21
#Mann=3,-1,0
  4790.1    0.07       0  4915.6    0.07       0  4921.0    0.07       0
Bank Sta=4915.6,4921
Exp/Cntr=0.3,0.1

Type RM Length L Ch R = 1,11254,498,498,498
BEGIN DESCRIPTION:
Sweetwater Creek Trib 9 22.0
END DESCRIPTION:
XS GIS Cut Line= 3
      1362904.99      6812038.04      1362971.49      6811770.89
      1362555.03      6811388.03
#Sta/Elev= 30
  4724.7 2447.48  4776.3 2441.32  4796.9 2433.26  4825.4 2426.67  4871.9 2424.73
  4889.6 2421.99  4913.2 2420.96  4944.1 2417.57  4949.4 2418.09  4954.5 2415.19
  4982.4 2410.26  4990.7 2407.56  5004.1 2406.99  5004.5 2406.49  5009.5 2406.99
  5027.8 2410.30  5049.4 2411.98  5056.2 2414.16  5191.4 2415.00  5218.9 2416.20
  5261.5 2424.09  5346.6 2429.45  5360.7 2434.84  5381.7 2431.39  5410.1 2432.17
  5452.6 2436.57  5481.0 2440.67  5509.3 2446.57  5562.3 2462.03  5565.7 2462.03
#Mann=5,-1,0
  4724.7    0.07       0  4944.1    0.16       0  5004.1    0.07       0
  5009.5    0.16       0  5191.4    0.07       0
Bank Sta=5004.1,5009.5
Exp/Cntr=0.3,0.1

Type RM Length L Ch R = 1,10756,494,494,494
BEGIN DESCRIPTION:
Sweetwater Creek Trib 9 21.0
END DESCRIPTION:
XS GIS Cut Line= 3
      1363404.99      6811737.97      1363288.32      6811454.22
      1363305.00      6811237.96
#Sta/Elev= 30
  4693.2 2428.68  4707.9 2428.03  4714.8 2425.50  4737.2 2420.27  4755.8 2418.69
  4798.5 2417.65  4814.5 2417.42  4833.1 2413.91  4838.5 2414.46  4844.5 2411.46
  4855.4 2409.51  4886.4 2408.90  4909.4 2409.88  4945.1 2409.52  4963.5 2407.01
  4993.0 2406.69  5021.6 2401.94  5026.6 2402.80  5033.5 2401.84  5034.0 2401.34
  5039.1 2401.84  5046.4 2404.47  5066.4 2421.58  5106.5 2427.89  5116.6 2431.04
  5151.8 2445.65  5156.8 2445.53  5196.8 2460.80  5215.5 2466.23  5216.9 2466.23
#Mann=5,-1,0
  4693.2    0.07       0  4798.5    0.16       0  5033.5    0.07       0
  5039.1    0.16       0  5215.5    0.07       0
Bank Sta=5033.5,5039.1
Exp/Cntr=0.3,0.1

Type RM Length L Ch R = 1,10262,497,497,497
BEGIN DESCRIPTION:
Sweetwater Creek Trib 9 20.0
END DESCRIPTION:
XS GIS Cut Line= 3
      1363654.99      6811588.05      1363701.67      6811340.92
      1363505.02      6811188.01
#Sta/Elev= 30
  4748.5 2414.88  4827.1 2411.72  4832.2 2412.22  4869.5 2409.57  4921.6 2412.12
  4931.7 2411.97  4937.0 2410.93  4942.1 2411.70  4952.1 2409.91  4989.4 2398.83
  4994.4 2401.57  4998.9 2398.98  5018.3 2397.34  5018.8 2396.84  5023.9 2397.34
  5034.7 2398.40  5042.8 2401.35  5057.3 2404.09  5078.1 2403.68  5148.7 2405.24
  5156.8 2407.92  5163.2 2411.18  5171.3 2416.03  5185.8 2427.10  5198.5 2449.06
  5206.6 2451.47  5212.9 2455.56  5227.4 2461.01  5235.5 2463.36  5249.1 2465.13
#Mann=4,-1,0
  4748.5   0.035       0  4869.5    0.07       0  5018.3    0.07       0
  5023.9    0.07       0
Bank Sta=5018.3,5023.9
Exp/Cntr=0.3,0.1

Type RM Length L Ch R = 1,9765,495,495,495
BEGIN DESCRIPTION:
Sweetwater Creek Trib 9 19.0
END DESCRIPTION:
XS GIS Cut Line= 3
      1363955.01      6811538.00      1364130.07      6811437.82
      1364155.00      6811337.99
#Sta/Elev= 30
  4798.3 2409.65  4806.2 2410.01  4861.7 2408.52  4865.2 2408.33  4878.9 2408.85
  4924.2 2407.04  4936.5 2405.03  4945.8 2404.57  4951.6 2401.06  4967.4 2397.56
  4973.2 2393.71  4982.6 2391.95  4989.0 2392.54  4991.9 2391.19  4992.3 2390.69
  4997.1 2390.69  4997.6 2391.19  5000.0 2392.47  5002.5 2392.47  5010.1 2393.96
  5020.4 2397.87  5043.6 2401.66  5051.4 2405.09  5061.7 2410.28  5072.0 2413.12
  5079.7 2414.06  5084.8 2417.25  5092.6 2420.27  5100.3 2422.64  5102.9 2422.64
#Mann=4,-1,0
  4798.3    0.07       0  4861.7    0.16       0  4991.9    0.07       0
  4997.6    0.16       0
Bank Sta=4991.9,4997.6
Exp/Cntr=0.3,0.1

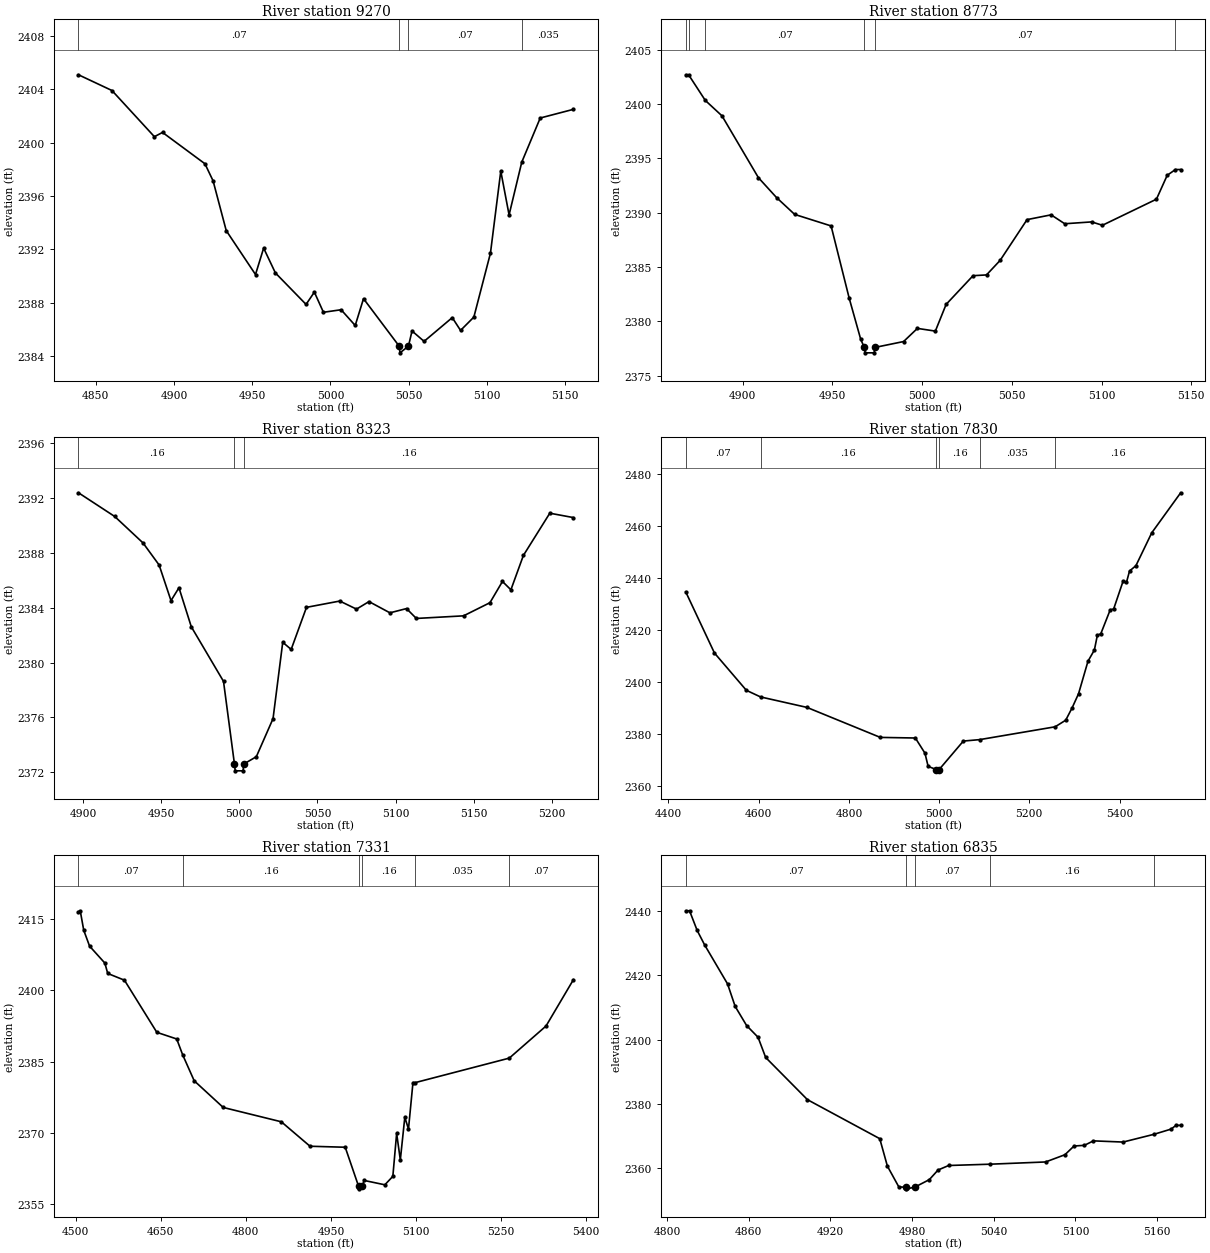
Type RM Length L Ch R = 1,9270,497,497,497
BEGIN DESCRIPTION:
Sweetwater Creek Trib 9 18.0
END DESCRIPTION:
XS GIS Cut Line= 3
      1364604.99      6811787.97      1364556.47      6811634.45
      1364505.01      6811488.03
#Sta/Elev= 30
  4839.0 2405.09  4860.4 2403.91  4887.5 2400.45  4892.7 2400.77  4919.8 2398.42
  4925.0 2397.14  4933.4 2393.41  4952.1 2390.12  4957.3 2392.10  4964.8 2390.24
  4984.4 2387.88  4989.7 2388.80  4995.5 2387.29  5006.8 2387.48  5015.8 2386.30
  5021.1 2388.31  5043.9 2384.75  5044.4 2384.25  5049.8 2384.75  5052.1 2385.89
  5059.8 2385.11  5077.8 2386.89  5083.1 2385.93  5091.6 2386.93  5102.2 2391.72
  5108.8 2397.87  5114.1 2394.59  5122.2 2398.54  5134.0 2401.85  5155.2 2402.50
#Mann=4,-1,0
  4839.0    0.07       0  5043.9    0.07       0  5049.8    0.07       0
  5122.2   0.035       0
Bank Sta=5043.9,5049.8
Exp/Cntr=0.3,0.1

Type RM Length L Ch R = 1,8773,450,450,450
BEGIN DESCRIPTION:
Sweetwater Creek Trib 9 17.0
END DESCRIPTION:
XS GIS Cut Line= 3
      1365005.00      6811588.01      1364985.00      6811457.84
      1364904.99      6811337.99
#Sta/Elev= 30
  4868.3 2402.69  4869.9 2402.69  4879.2 2400.33  4888.5 2398.91  4908.8 2393.22
  4918.9 2391.39  4929.0 2389.84  4949.3 2388.78  4959.4 2382.12  4965.8 2378.35
  4967.8 2377.60  4968.3 2377.10  4973.3 2377.10  4973.8 2377.60  4989.7 2378.14
  4997.4 2379.35  5007.4 2379.10  5013.4 2381.56  5028.4 2384.20  5035.9 2384.27
  5043.5 2385.61  5058.5 2389.36  5071.9 2389.80  5079.5 2388.98  5094.5 2389.15
  5100.5 2388.84  5130.6 2391.24  5136.6 2393.44  5141.2 2393.97  5144.1 2393.97
#Mann=6,-1,0
  4868.3    0.07       0  4869.9    0.16       0  4879.2    0.07       0
  4967.8    0.07       0  4973.8    0.07       0  5141.2   0.035       0
Bank Sta=4967.8,4973.8
Exp/Cntr=0.3,0.1

Type RM Length L Ch R = 1,8323,493,493,493
BEGIN DESCRIPTION:
Sweetwater Creek Trib 9 16.0
END DESCRIPTION:
XS GIS Cut Line= 3
      1365354.99      6811588.02      1365380.07      6811488.23
      1365305.01      6811288.04
#Sta/Elev= 30
  4897.1 2392.39  4920.3 2390.66  4938.4 2388.73  4948.7 2387.12  4956.3 2384.52
  4961.4 2385.46  4969.3 2382.61  4989.9 2378.63  4996.9 2372.60  4997.4 2372.10
  5002.4 2372.10  5002.9 2372.60  5010.9 2373.13  5021.6 2375.91  5027.8 2381.48
  5033.2 2380.96  5043.0 2384.03  5064.3 2384.49  5075.0 2383.90  5083.0 2384.45
  5096.4 2383.63  5107.0 2383.94  5113.3 2383.22  5143.5 2383.41  5160.4 2384.37
  5168.4 2385.92  5173.8 2385.31  5181.8 2387.82  5198.7 2390.90  5213.8 2390.58
#Mann=3,-1,0
  4897.1    0.16       0  4996.9    0.07       0  5002.9    0.16       0
Bank Sta=4996.9,5002.9
Exp/Cntr=0.3,0.1

Type RM Length L Ch R = 1,7830,499,499,499
BEGIN DESCRIPTION:
Sweetwater Creek Trib 9 15.0
END DESCRIPTION:
XS GIS Cut Line= 3
      1366155.01      6811638.01      1365758.99      6811239.68
      1365355.01      6810888.01
#Sta/Elev= 30
  4438.3 2434.67  4502.0 2411.08  4572.7 2396.71  4604.1 2394.16  4707.0 2390.12
  4869.7 2378.55  4947.4 2378.32  4968.7 2372.46  4975.7 2367.38  4993.7 2366.16
  4994.2 2365.66  5000.1 2366.16  5053.8 2377.14  5090.2 2377.70  5257.3 2382.64
  5280.7 2385.18  5294.9 2389.93  5309.2 2395.39  5330.1 2407.92  5344.3 2412.25
  5350.9 2417.94  5358.5 2418.50  5379.4 2427.74  5387.0 2428.05  5407.9 2438.77
  5415.5 2438.36  5422.2 2442.69  5436.4 2444.77  5471.5 2457.44  5535.6 2472.87
#Mann=6,-1,0
  4438.3    0.07       0  4604.1    0.16       0  4993.7    0.07       0
  5000.1    0.16       0  5090.2   0.035       0  5257.3    0.16       0
Bank Sta=4993.7,5000.1
Exp/Cntr=0.3,0.1

Type RM Length L Ch R = 1,7331,496,496,496
BEGIN DESCRIPTION:
Sweetwater Creek Trib 9 14.0
END DESCRIPTION:
XS GIS Cut Line= 3
      1366250.46      6811507.11      1366141.96      6811023.94
      1365902.77      6810731.50
#Sta/Elev= 30
  4504.8 2416.41  4507.9 2416.75  4514.1 2412.64  4524.4 2409.30  4551.3 2405.74
  4556.4 2403.55  4585.9 2402.13  4643.0 2391.15  4678.1 2389.75  4688.5 2386.44
  4708.9 2380.95  4760.1 2375.33  4862.6 2372.31  4913.2 2367.16  4975.3 2366.95
  4999.0 2358.69  4999.5 2358.19  5005.4 2358.69  5008.6 2359.96  5045.2 2359.04
  5059.3 2360.82  5066.0 2369.86  5072.5 2364.29  5080.4 2373.26  5086.9 2370.79
  5094.8 2380.58  5097.8 2380.53  5264.7 2385.72  5329.5 2392.48  5377.8 2402.24
#Mann=6,-1,0
  4504.8    0.07       0  4688.5    0.16       0  4999.0    0.07       0
  5005.4    0.16       0  5097.8   0.035       0  5264.7    0.07       0
Bank Sta=4999,5005.4
Exp/Cntr=0.3,0.1

Type RM Length L Ch R = 1,6835,379,379,379
BEGIN DESCRIPTION:
Sweetwater Creek Trib 9 13.0
END DESCRIPTION:
XS GIS Cut Line= 3
      1366654.99      6811237.97      1366571.71      6811071.43
      1366454.98      6810937.98
#Sta/Elev= 30
  4813.8 2440.05  4816.6 2440.05  4822.2 2433.93  4827.7 2429.41  4844.5 2417.32
  4850.1 2410.31  4858.5 2404.36  4866.9 2400.72  4872.5 2394.43  4903.2 2381.30
  4956.3 2369.17  4961.9 2360.64  4970.3 2354.17  4975.4 2354.07  4975.9 2353.57
  4981.9 2354.07  4992.7 2356.43  4999.1 2359.42  5006.9 2360.83  5037.1 2361.23
  5078.1 2361.93  5092.3 2364.18  5099.0 2366.89  5106.6 2367.10  5113.2 2368.49
  5135.0 2368.12  5157.6 2370.52  5170.2 2372.14  5173.9 2373.32  5177.3 2373.32
#Mann=5,-1,0
  4813.8    0.07       0  4975.4    0.07       0  4981.9    0.07       0
  5037.1    0.16       0  5157.6    0.07       0
Bank Sta=4975.4,4981.9
Exp/Cntr=0.3,0.1

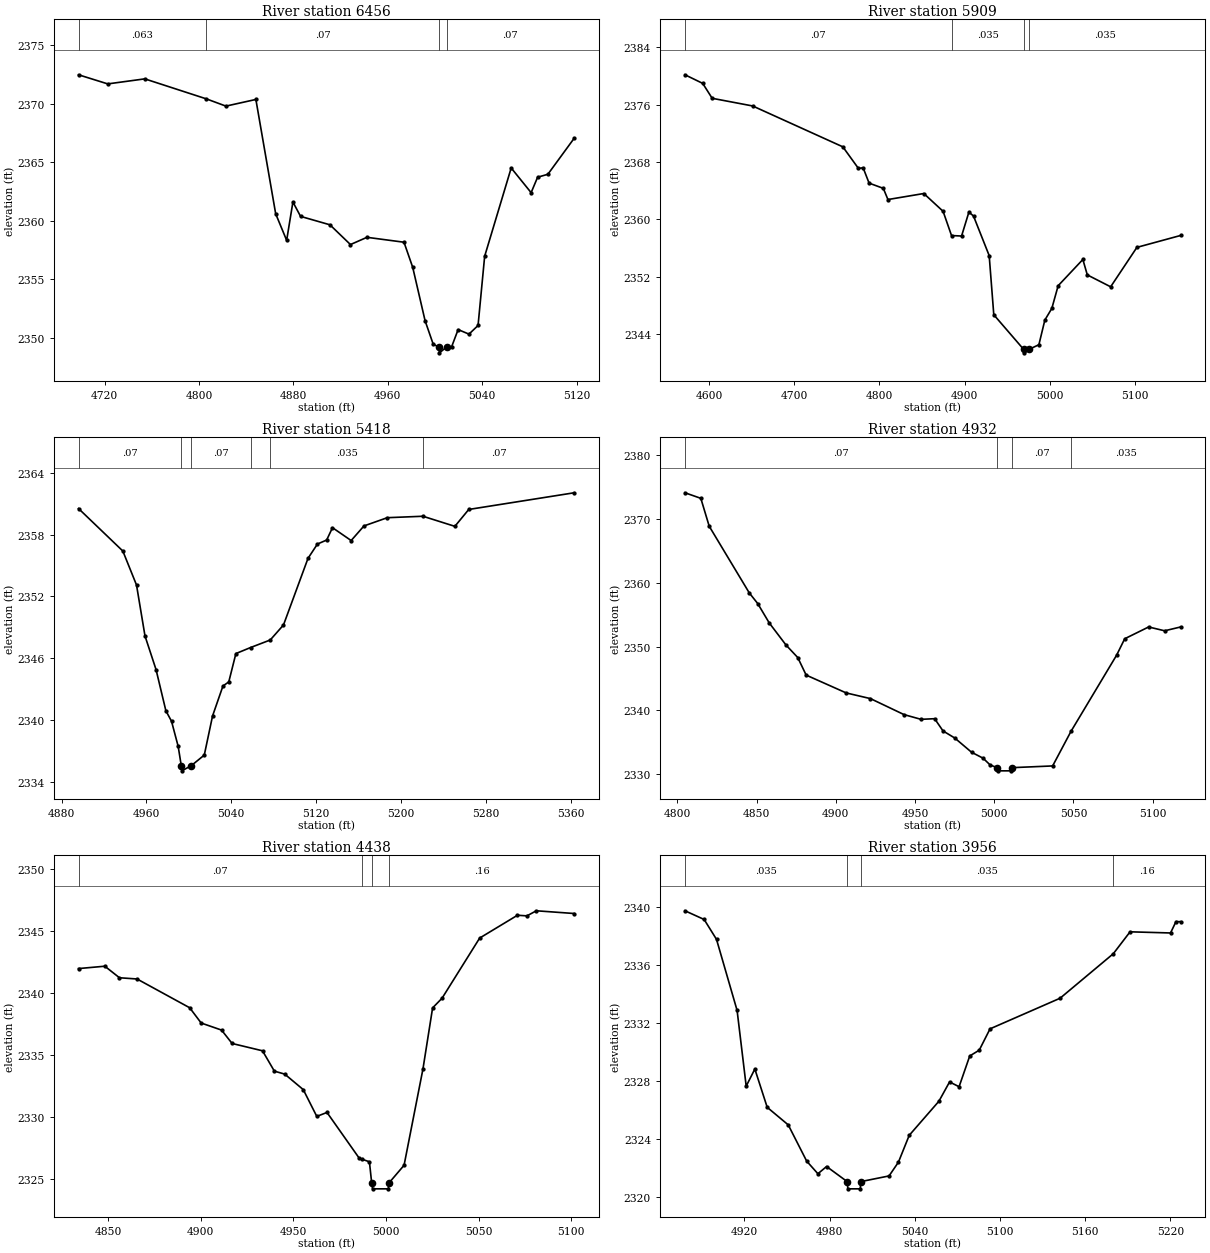
Type RM Length L Ch R = 1,6456,547,547,547
BEGIN DESCRIPTION:
Sweetwater Creek Trib 9 12.0
END DESCRIPTION:
XS GIS Cut Line= 3
      1366958.02      6811126.32      1366860.86      6810840.06
      1366754.97      6810787.99
#Sta/Elev= 30
  4697.7 2372.47  4722.5 2371.69  4753.9 2372.12  4806.1 2370.41  4822.7 2369.79
  4848.1 2370.36  4864.9 2360.58  4874.2 2358.31  4879.5 2361.59  4886.0 2360.36
  4910.9 2359.64  4928.3 2357.95  4942.3 2358.57  4973.7 2358.15  4981.1 2356.00
  4991.6 2351.43  4998.5 2349.42  5003.3 2349.19  5003.8 2348.69  5009.8 2349.19
  5014.1 2349.21  5019.6 2350.68  5028.8 2350.29  5036.5 2351.03  5042.1 2356.95
  5064.6 2364.50  5081.5 2362.39  5087.0 2363.71  5095.7 2363.96  5118.0 2367.04
#Mann=4,-1,0
  4697.7   0.063       0  4806.1    0.07       0  5003.3    0.07       0
  5009.8    0.07       0
Bank Sta=5003.3,5009.8
Exp/Cntr=0.3,0.1

Type RM Length L Ch R = 1,5909,491,491,491
BEGIN DESCRIPTION:
Sweetwater Creek Trib 9 11.0
END DESCRIPTION:
XS GIS Cut Line= 3
      1367370.37      6810967.15      1367204.37      6810572.44
      1367054.99      6810538.00
#Sta/Elev= 30
  4571.8 2380.16  4592.6 2378.96  4603.7 2376.88  4651.2 2375.81  4757.0 2370.11
  4775.3 2367.10  4780.8 2367.19  4787.8 2365.05  4804.5 2364.32  4809.9 2362.76
  4852.0 2363.60  4874.6 2361.12  4884.5 2357.74  4896.3 2357.67  4904.9 2361.01
  4910.3 2360.46  4928.7 2354.94  4934.1 2346.69  4969.0 2341.88  4969.5 2341.38
  4975.6 2341.88  4987.0 2342.51  4994.0 2345.95  5002.2 2347.58  5009.6 2350.74
  5038.6 2354.40  5043.8 2352.25  5071.2 2350.59  5102.0 2356.09  5153.3 2357.75
#Mann=4,-1,0
  4571.8    0.07       0  4884.5   0.035       0  4969.0   0.035       0
  4975.6   0.035       0
Bank Sta=4969,4975.6
Exp/Cntr=0.3,0.1

Type RM Length L Ch R = 1,5418,486,486,486
BEGIN DESCRIPTION:
Sweetwater Creek Trib 9 10.0
END DESCRIPTION:
XS GIS Cut Line= 3
      1367605.00      6810637.99      1367635.05      6810538.42
      1367484.94      6810207.48
#Sta/Elev= 30
  4896.0 2360.53  4937.8 2356.40  4950.7 2353.10  4958.7 2348.15  4969.1 2344.89
  4978.4 2340.88  4983.7 2339.87  4990.0 2337.42  4992.9 2335.55  4993.4 2335.05
  5002.3 2335.55  5014.6 2336.58  5022.4 2340.38  5032.2 2343.29  5037.7 2343.69
  5044.4 2346.44  5058.3 2347.03  5076.8 2347.76  5089.3 2349.22  5112.4 2355.69
  5121.3 2357.08  5130.0 2357.47  5135.5 2358.67  5153.1 2357.42  5165.2 2358.84
  5187.2 2359.64  5220.8 2359.78  5250.9 2358.80  5264.0 2360.44  5363.4 2362.06
#Mann=6,-1,0
  4896.0    0.07       0  4992.9    0.07       0  5002.3    0.07       0
  5058.3    0.16       0  5076.8   0.035       0  5220.8    0.07       0
Bank Sta=4992.9,5002.3
Exp/Cntr=0.3,0.1

Type RM Length L Ch R = 1,4932,494,494,494
BEGIN DESCRIPTION:
Sweetwater Creek Trib 9 9.0
END DESCRIPTION:
XS GIS Cut Line= 3
      1367905.00      6810588.01      1367971.70      6810404.56
      1367955.01      6810288.05
#Sta/Elev= 30
  4804.8 2374.15  4814.8 2373.28  4820.1 2368.90  4845.4 2358.44  4850.7 2356.78
  4858.0 2353.73  4868.6 2350.26  4876.0 2348.30  4881.3 2345.55  4906.6 2342.75
  4921.9 2341.86  4943.1 2339.35  4953.8 2338.61  4962.4 2338.71  4967.7 2336.79
  4975.1 2335.68  4985.7 2333.45  4993.0 2332.51  4997.5 2331.44  5001.9 2331.03
  5002.4 2330.53  5010.9 2330.53  5011.4 2331.03  5036.9 2331.30  5048.5 2336.73
  5077.3 2348.68  5082.4 2351.25  5097.5 2353.10  5107.6 2352.50  5117.7 2353.10
#Mann=4,-1,0
  4804.8    0.07       0  5001.9    0.07       0  5011.4    0.07       0
  5048.5   0.035       0
Bank Sta=5001.9,5011.4
Exp/Cntr=0.3,0.1

Type RM Length L Ch R = 1,4438,482,482,482
BEGIN DESCRIPTION:
Sweetwater Creek Trib 9 8.0
END DESCRIPTION:
XS GIS Cut Line= 3
      1368305.00      6810588.00      1368374.97      6810437.58
      1368354.99      6810337.96
#Sta/Elev= 30
  4834.1 2341.94  4848.3 2342.13  4856.2 2341.20  4865.7 2341.10  4894.1 2338.78
  4900.3 2337.55  4911.3 2336.98  4917.0 2335.90  4933.4 2335.31  4939.8 2333.67
  4945.4 2333.43  4955.4 2332.18  4962.7 2330.02  4968.2 2330.34  4985.6 2326.65
  4986.9 2326.58  4991.1 2326.36  4992.3 2324.68  4992.8 2324.18  5001.3 2324.18
  5001.8 2324.68  5009.8 2326.08  5020.0 2333.85  5025.2 2338.77  5030.3 2339.55
  5050.6 2344.40  5071.0 2346.24  5076.1 2346.19  5081.2 2346.60  5101.6 2346.38
#Mann=4,-1,0
  4834.1    0.07       0  4986.9    0.16       0  4992.3    0.07       0
  5001.8    0.16       0
Bank Sta=4992.3,5001.8
Exp/Cntr=0.3,0.1

Type RM Length L Ch R = 1,3956,498,498,498
BEGIN DESCRIPTION:
Sweetwater Creek Trib 9 7.0
END DESCRIPTION:
XS GIS Cut Line= 3
      1368754.98      6810538.02      1368825.21      6810438.50
      1368655.00      6810288.00
#Sta/Elev= 30
  4878.2 2339.71  4891.7 2339.11  4900.4 2337.74  4914.9 2332.84  4921.3 2327.62
  4927.4 2328.80  4936.1 2326.16  4950.9 2324.95  4963.9 2322.45  4971.8 2321.58
  4977.9 2322.08  4992.4 2321.04  4992.9 2320.54  5001.6 2320.54  5002.1 2321.04
  5021.9 2321.43  5028.5 2322.38  5036.1 2324.23  5057.0 2326.58  5064.5 2327.91
  5071.2 2327.58  5078.7 2329.70  5085.4 2330.10  5093.0 2331.57  5142.3 2333.68
  5179.8 2336.75  5191.6 2338.26  5220.1 2338.18  5223.9 2338.96  5227.2 2338.96
#Mann=4,-1,0
  4878.2   0.035       0  4992.4   0.035       0  5002.1   0.035       0
  5179.8    0.16       0
Bank Sta=4992.4,5002.1
Exp/Cntr=0.3,0.1