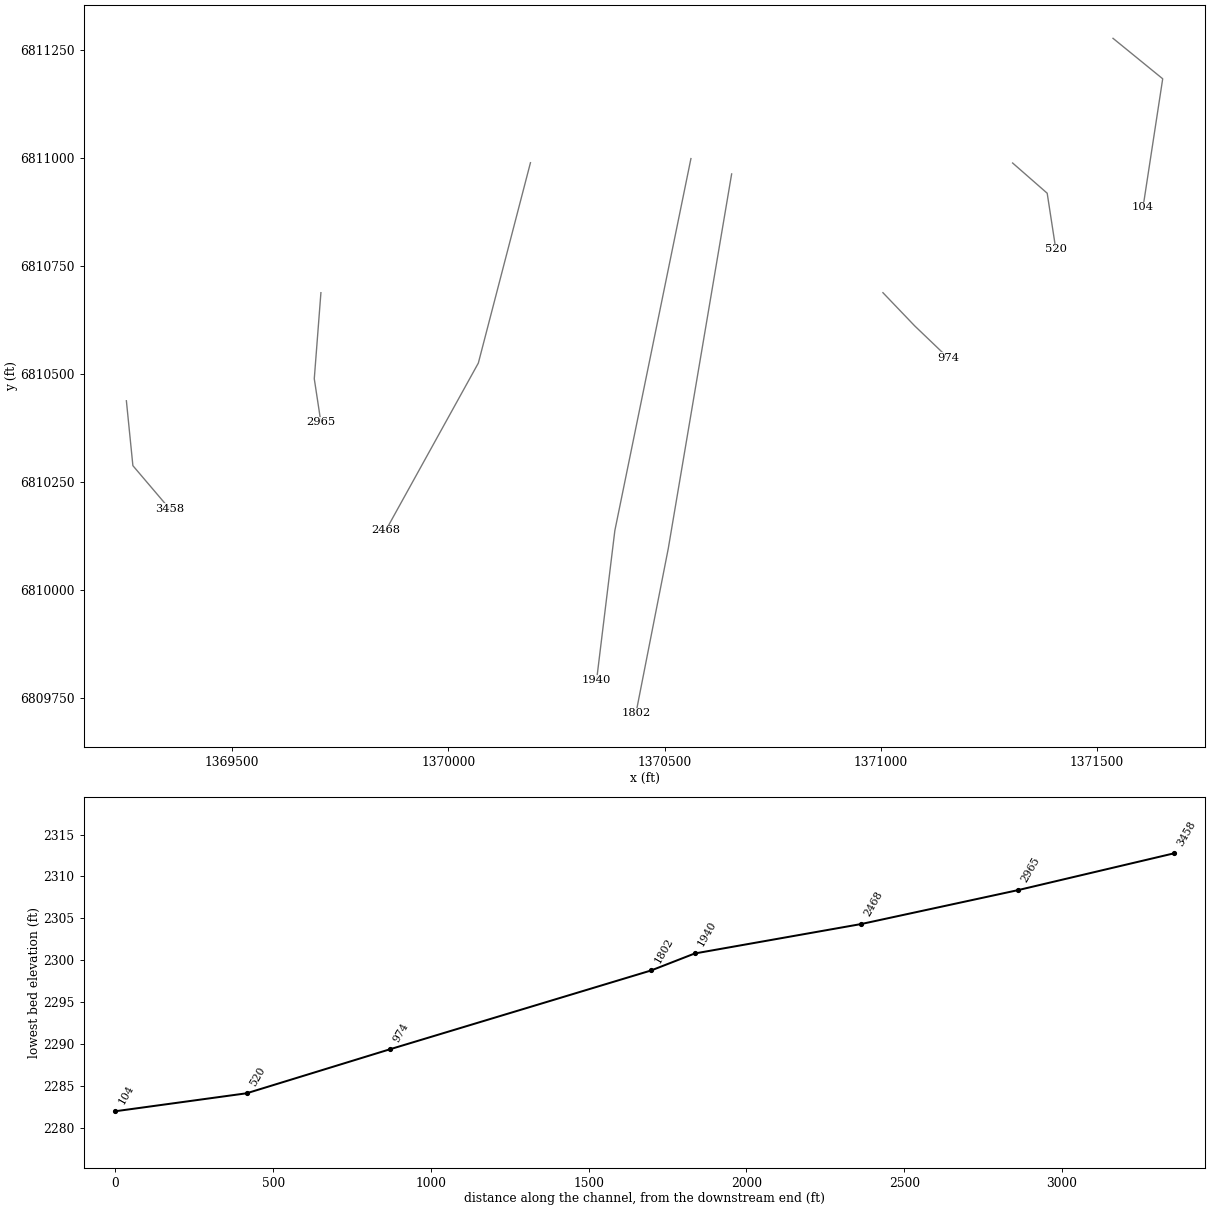
HEC-RAS study Sweetwater Creek Trib 9.prj: Sweetwater Creek Trib 9 Base Level Engineering

--- Sweetwater Creek Trib 9.g01 (geometry) --- (continued)

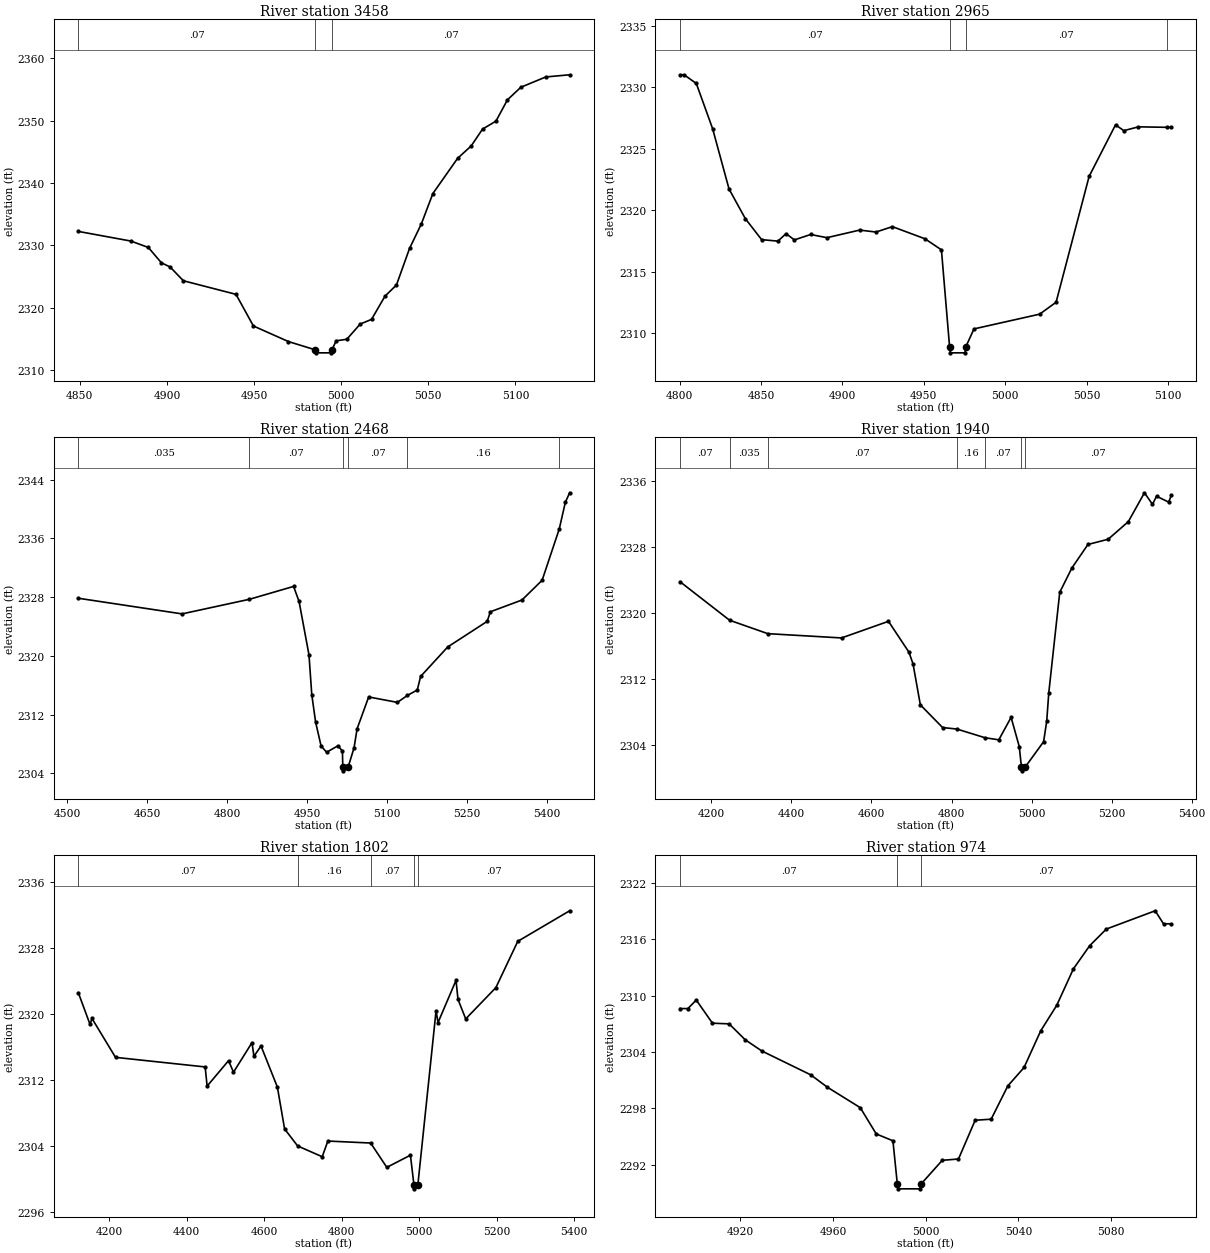
Type RM Length L Ch R = 1,3458,493,493,493
BEGIN DESCRIPTION:
Sweetwater Creek Trib 9 6.0
END DESCRIPTION:
XS GIS Cut Line= 3
      1369255.00      6810438.00      1369270.06      6810287.86
      1369355.00      6810188.00
#Sta/Elev= 30
  4849.1 2332.24  4879.3 2330.69  4889.3 2329.66  4896.8 2327.20  4901.8 2326.53
  4909.4 2324.32  4939.6 2322.14  4949.6 2317.06  4969.7 2314.56  4984.9 2313.25
  4985.4 2312.75  4994.2 2312.75  4994.7 2313.25  4997.1 2314.68  5003.2 2314.93
  5010.9 2317.37  5017.4 2318.12  5025.1 2321.84  5031.7 2323.64  5039.2 2329.50
  5046.0 2333.45  5052.6 2338.32  5066.8 2343.97  5074.6 2345.96  5081.1 2348.66
  5088.8 2349.94  5095.4 2353.36  5103.1 2355.38  5117.4 2357.03  5131.1 2357.38
#Mann=3,-1,0
  4849.1    0.07       0  4984.9    0.07       0  4994.7    0.07       0
Bank Sta=4984.9,4994.7
Exp/Cntr=0.3,0.1

Type RM Length L Ch R = 1,2965,497,497,497
BEGIN DESCRIPTION:
Sweetwater Creek Trib 9 5.0
END DESCRIPTION:
XS GIS Cut Line= 3
      1369705.00      6810687.98      1369689.64      6810488.87
      1369704.99      6810388.03
#Sta/Elev= 30
  4800.3 2331.03  4802.8 2331.03  4810.3 2330.32  4820.3 2326.64  4830.4 2321.72
  4840.4 2319.31  4850.4 2317.60  4860.4 2317.48  4865.4 2318.09  4870.5 2317.58
  4880.5 2318.02  4890.5 2317.76  4910.6 2318.38  4920.6 2318.22  4930.7 2318.66
  4950.7 2317.67  4960.8 2316.77  4965.8 2308.88  4966.3 2308.38  4975.3 2308.38
  4975.8 2308.88  4980.8 2310.33  5021.1 2311.53  5031.2 2312.50  5051.5 2322.76
  5067.7 2326.95  5072.8 2326.48  5081.8 2326.79  5099.2 2326.75  5102.0 2326.75
#Mann=4,-1,0
  4800.3    0.07       0  4965.8    0.07       0  4975.8    0.07       0
  5099.2    0.16       0
Bank Sta=4965.8,4975.8
Exp/Cntr=0.3,0.1

Type RM Length L Ch R = 1,2468,528,528,528
BEGIN DESCRIPTION:
Sweetwater Creek Trib 9 4.0
END DESCRIPTION:
XS GIS Cut Line= 3
      1370189.70      6810988.67      1370069.14      6810525.19
      1369854.98      6810137.97
#Sta/Elev= 30
  4521.1 2327.84  4715.7 2325.71  4842.1 2327.70  4924.8 2329.45  4935.1 2327.40
  4953.7 2320.12  4958.9 2314.73  4966.1 2310.98  4976.4 2307.72  4986.8 2306.87
  5008.2 2307.76  5016.4 2307.02  5017.1 2304.84  5017.6 2304.34  5027.1 2304.84
  5038.2 2307.48  5043.9 2310.06  5065.6 2314.40  5119.5 2313.66  5138.1 2314.60
  5156.8 2315.35  5163.0 2317.19  5213.9 2321.21  5287.8 2324.69  5293.9 2326.00
  5353.1 2327.60  5390.9 2330.29  5423.0 2337.27  5434.4 2340.90  5442.5 2342.20
#Mann=6,-1,0
  4521.1   0.035       0  4842.1    0.07       0  5017.1    0.07       0
  5027.1    0.07       0  5138.1    0.16       0  5423.0    0.07       0
Bank Sta=5017.1,5027.1
Exp/Cntr=0.3,0.1

Type RM Length L Ch R = 1,1940,138,138,138
BEGIN DESCRIPTION:
Sweetwater Creek Trib 9 3.0
END DESCRIPTION:
XS GIS Cut Line= 3
      1370560.90      6810998.18      1370384.92      6810137.79
      1370342.59      6809791.17
#Sta/Elev= 30
  4121.8 2323.81  4245.6 2319.13  4341.0 2317.50  4525.3 2316.98  4642.5 2319.00
  4693.6 2315.25  4703.8 2313.83  4722.1 2308.85  4777.7 2306.09  4813.3 2305.91
  4883.8 2304.85  4918.1 2304.60  4948.8 2307.33  4969.2 2303.78  4974.5 2301.33
  4975.0 2300.83  4984.6 2301.33  5030.0 2304.37  5037.8 2306.87  5042.9 2310.30
  5070.3 2322.52  5100.5 2325.47  5140.8 2328.34  5191.2 2328.97  5241.6 2331.11
  5281.9 2334.62  5302.0 2333.21  5312.1 2334.20  5342.3 2333.49  5349.2 2334.31
#Mann=7,-1,0
  4121.8    0.07       0  4245.6   0.035       0  4341.0    0.07       0
  4813.3    0.16       0  4883.8    0.07       0  4974.5    0.07       0
  4984.6    0.07       0
Bank Sta=4974.5,4984.6
Exp/Cntr=0.3,0.1

Type RM Length L Ch R = 1,1802,828,828,828
BEGIN DESCRIPTION:
Sweetwater Creek Trib 9 2.0
END DESCRIPTION:
XS GIS Cut Line= 3
      1370655.07      6810962.69      1370508.41      6810095.81
      1370433.61      6809714.88
#Sta/Elev= 30
  4120.8 2322.58  4151.0 2318.74  4156.1 2319.45  4216.8 2314.74  4448.0 2313.58
  4453.1 2311.26  4508.4 2314.34  4521.1 2312.94  4568.8 2316.52  4573.9 2314.87
  4592.1 2316.12  4634.3 2311.14  4652.9 2306.07  4686.5 2304.01  4750.0 2302.70
  4764.5 2304.60  4874.9 2304.36  4916.6 2301.41  4977.5 2302.89  4986.5 2299.31
  4987.0 2298.81  4996.7 2299.31  5043.6 2320.37  5048.7 2318.96  5095.1 2324.07
  5100.2 2321.76  5120.1 2319.40  5197.9 2323.19  5254.4 2328.80  5388.2 2332.50
#Mann=5,-1,0
  4120.8    0.07       0  4686.5    0.16       0  4874.9    0.07       0
  4986.5    0.07       0  4996.7    0.07       0
Bank Sta=4986.5,4996.7
Exp/Cntr=0.3,0.1

Type RM Length L Ch R = 1,974,454,454,454
BEGIN DESCRIPTION:
Sweetwater Creek Trib 9 1.0
END DESCRIPTION:
XS GIS Cut Line= 3
      1371005.03      6810687.97      1371078.38      6810611.31
      1371154.97      6810538.03
#Sta/Elev= 30
  4893.9 2308.63  4897.3 2308.63  4900.9 2309.54  4907.9 2307.07  4915.1 2307.00
  4922.0 2305.31  4929.2 2304.11  4950.3 2301.57  4957.5 2300.25  4971.7 2298.07
  4978.6 2295.27  4985.8 2294.54  4987.7 2289.92  4988.2 2289.42  4997.4 2289.42
  4997.9 2289.92  5007.1 2292.46  5014.1 2292.60  5021.3 2296.73  5028.2 2296.84
  5035.4 2300.39  5042.4 2302.35  5049.6 2306.26  5056.5 2308.97  5063.7 2312.86
  5070.7 2315.32  5077.9 2317.10  5099.0 2319.05  5102.6 2317.66  5106.0 2317.66
#Mann=3,-1,0
  4893.9    0.07       0  4987.7    0.07       0  4997.9    0.07       0
Bank Sta=4987.7,4997.9
Exp/Cntr=0.3,0.1

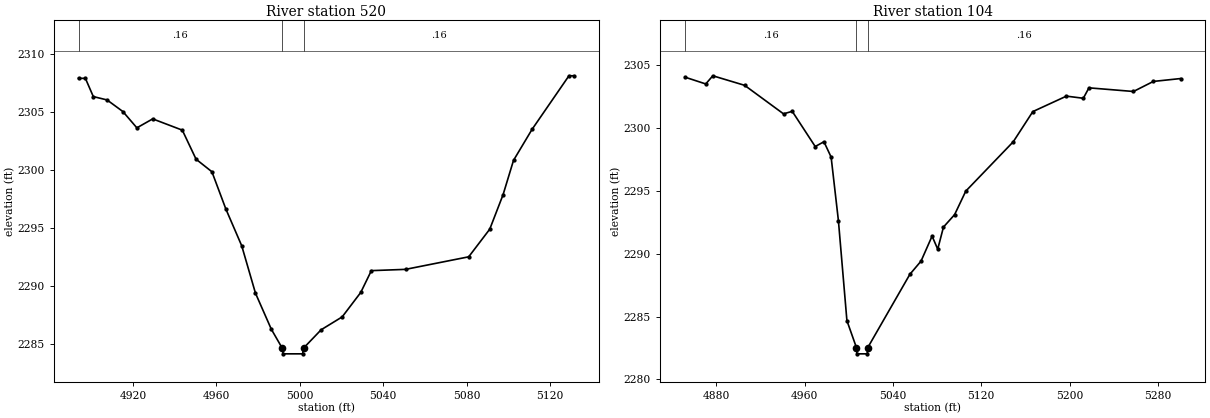
Type RM Length L Ch R = 1,520,416,416,416
BEGIN DESCRIPTION:
Sweetwater Creek Trib 9 0.1
END DESCRIPTION:
XS GIS Cut Line= 3
      1371305.02      6810987.98      1371384.97      6810918.07
      1371405.00      6810788.01
#Sta/Elev= 30
  4893.8 2307.89  4897.1 2307.89  4900.9 2306.32  4907.5 2306.03  4915.1 2305.03
  4921.8 2303.63  4929.4 2304.40  4943.6 2303.43  4950.2 2300.93  4957.8 2299.85
  4964.5 2296.64  4972.1 2293.48  4978.7 2289.40  4986.3 2286.30  4991.5 2284.68
  4992.0 2284.18  5001.3 2284.18  5001.8 2284.68  5010.2 2286.25  5020.3 2287.36
  5029.2 2289.46  5034.3 2291.34  5050.7 2291.45  5081.0 2292.53  5091.1 2294.91
  5097.5 2297.88  5102.5 2300.83  5111.4 2303.50  5129.1 2308.11  5131.6 2308.11
#Mann=3,-1,0
  4893.8    0.16       0  4991.5    0.07       0  5001.8    0.16       0
Bank Sta=4991.5,5001.8
Exp/Cntr=0.3,0.1

Type RM Length L Ch R = 1,104,0,0,0
BEGIN DESCRIPTION:
Sweetwater Creek Trib 9 4404
END DESCRIPTION:
XS GIS Cut Line= 3
      1371537.25      6811276.35      1371652.18      6811182.78
      1371606.70      6810885.75
#Sta/Elev= 30
  4851.8 2304.06  4870.6 2303.52  4877.0 2304.17  4905.8 2303.41  4941.0 2301.14
  4948.9 2301.34  4969.7 2298.54  4977.6 2298.92  4984.1 2297.70  4990.7 2292.64
  4998.4 2284.68  5007.0 2282.54  5007.5 2282.04  5016.8 2282.04  5017.3 2282.54
  5055.4 2288.37  5065.5 2289.42  5075.5 2291.41  5080.6 2290.37  5085.8 2292.13
  5095.9 2293.12  5106.0 2294.99  5149.0 2298.92  5166.7 2301.32  5197.1 2302.55
  5212.4 2302.38  5217.5 2303.21  5257.8 2302.92  5275.8 2303.72  5300.5 2303.95
#Mann=3,-1,0
  4851.8    0.16       0  5007.0    0.07       0  5017.3    0.16       0
Bank Sta=5007,5017.3
Exp/Cntr=0.3,0.1

Chan Stop Cuts=-1