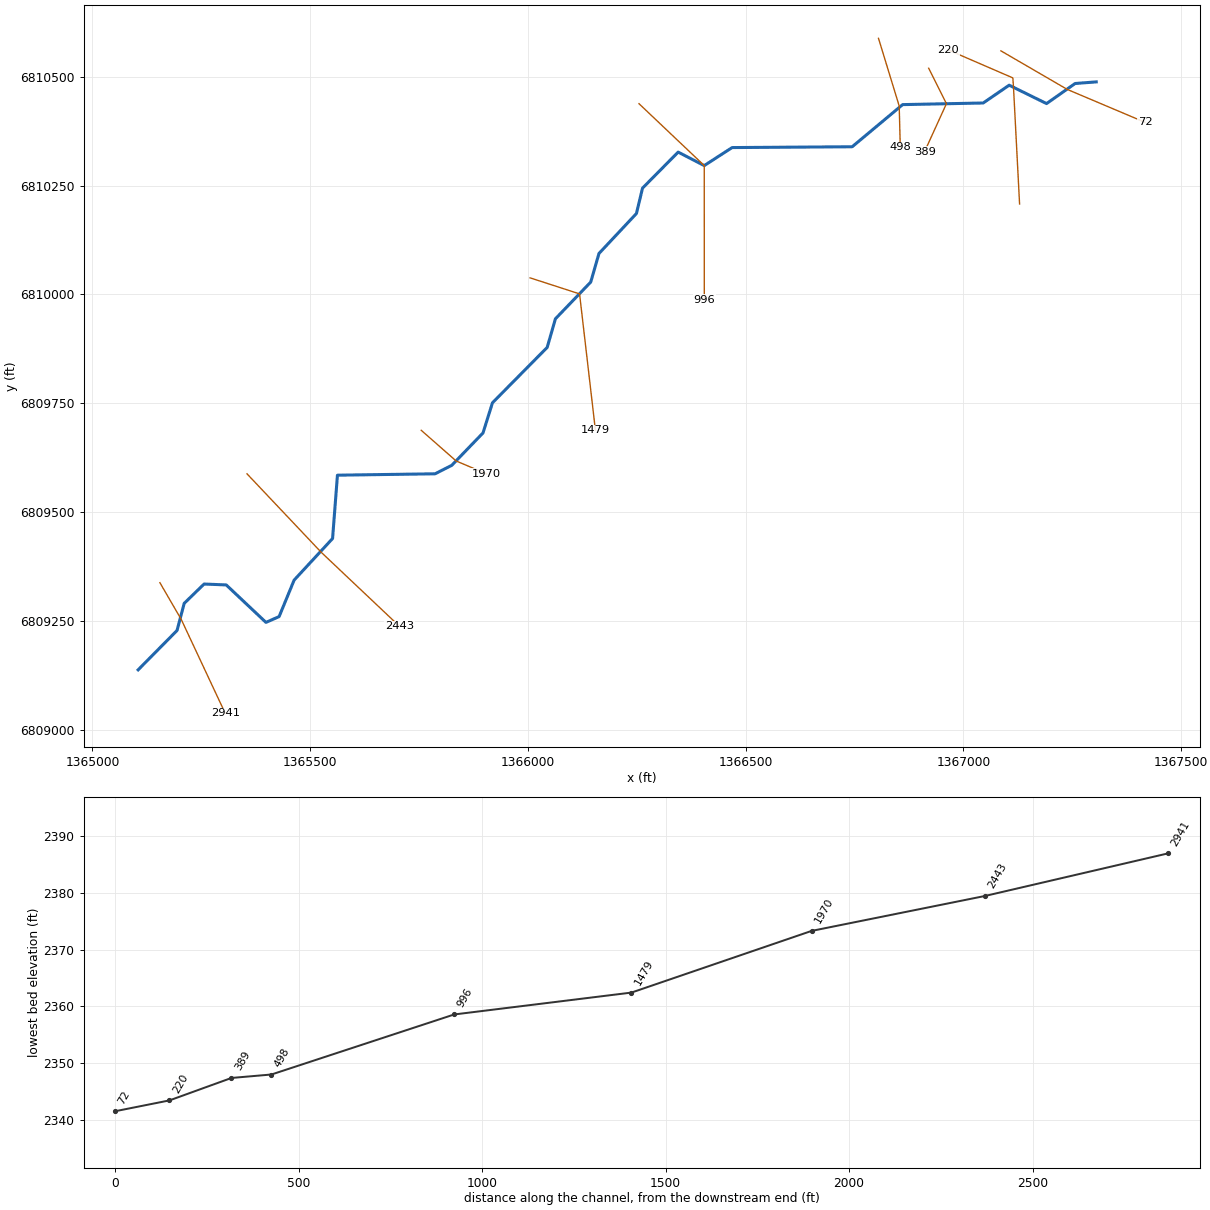
--- Sweetwater Creek Trib 9 T.prj (project) ---

Proj Title=Sweetwater Creek Trib 9 T Base Level Engineering
Current Plan=p01
Default Exp/Contr=0.3,0.1
English Units
Geom File=g01
Flow File=f01
Plan File=p01
BEGIN DESCRIPTION:
Sweetwater Creek Trib 9 T
END DESCRIPTION:

--- Sweetwater Creek Trib 9 T.p01 (plan) ---

Plan Title=Multiple Run
Short Identifier=Multiple
Geom File=g01
Flow File=f01
Subcritical Flow
K Sum by GR= 0
Std Step Tol= 0.01
Critical Tol= 0.01
Num of Std Step Trials= 20
Max Error Tol= 0.3
Flow Tol Ratio= 0.001
Split Flow NTrial= 30
Split Flow Tol= 0.02
Split Flow Ratio= 0.02
Log Output Level= 0
Friction Slope Method= 1
Unsteady Friction Slope Method= 2
Unsteady Bridges Friction Slope Method= 1
Parabolic Critical Depth
Global Vel Dist=  1 , 1 , 1
Global Log Level= 0
CheckData=True
Encroach Param= -1, 0, 0, 0
BEGIN DESCRIPTION:
Multiple Run
END DESCRIPTION:

--- Sweetwater Creek Trib 9 T.f01 (steady flow) ---

Flow Title=Multiple
Number of Profiles=7
Profile Names=10-year,25-year,50-year,1pct_min,100-year,1pct_plu,500-year
River Rch & RM= Sweetwater Creek,Reach-1,2941
     319     459     579     364     725    1447    1153
Boundary for River Rch & Prof#=Sweetwater Creek,Reach-1,1
Up Type=0
Dn Type=3
Dn Slope=0.005
Boundary for River Rch & Prof#=Sweetwater Creek,Reach-1,2
Up Type=0
Dn Type=3
Dn Slope=0.005
Boundary for River Rch & Prof#=Sweetwater Creek,Reach-1,3
Up Type=0
Dn Type=3
Dn Slope=0.005
Boundary for River Rch & Prof#=Sweetwater Creek,Reach-1,4
Up Type=0
Dn Type=3
Dn Slope=0.005
Boundary for River Rch & Prof#=Sweetwater Creek,Reach-1,5
Up Type=0
Dn Type=3
Dn Slope=0.005
Boundary for River Rch & Prof#=Sweetwater Creek,Reach-1,6
Up Type=0
Dn Type=3
Dn Slope=0.005
Boundary for River Rch & Prof#=Sweetwater Creek,Reach-1,7
Up Type=0
Dn Type=3
Dn Slope=0.005

--- Sweetwater Creek Trib 9 T.g01 (geometry) ---

Geom Title=Existing Conditions

River Reach=Sweetwater Creek,Reach-1
Reach XY= 30
      1365105.00      6809138.00      1365194.28      6809228.32
      1365210.74      6809290.62      1365256.43      6809334.99
      1365307.27      6809332.92      1365398.49      6809246.91
      1365428.70      6809260.23      1365463.18      6809344.00
      1365551.44      6809439.48      1365562.62      6809584.93
      1365786.79      6809588.09      1365825.20      6809607.59
      1365896.85      6809681.93      1365918.63      6809751.21
      1366044.22      6809878.32      1366063.18      6809944.04
      1366144.20      6810028.33      1366163.18      6810094.04
      1366249.13      6810185.72      1366263.16      6810244.09
      1366344.98      6810326.77      1366404.90      6810295.81
      1366468.86      6810337.18      1366744.56      6810339.06
      1366860.45      6810435.82      1367045.41      6810439.55
      1367105.01      6810480.41      1367190.89      6810438.18
      1367256.49      6810484.31      1367305.00      6810488.00

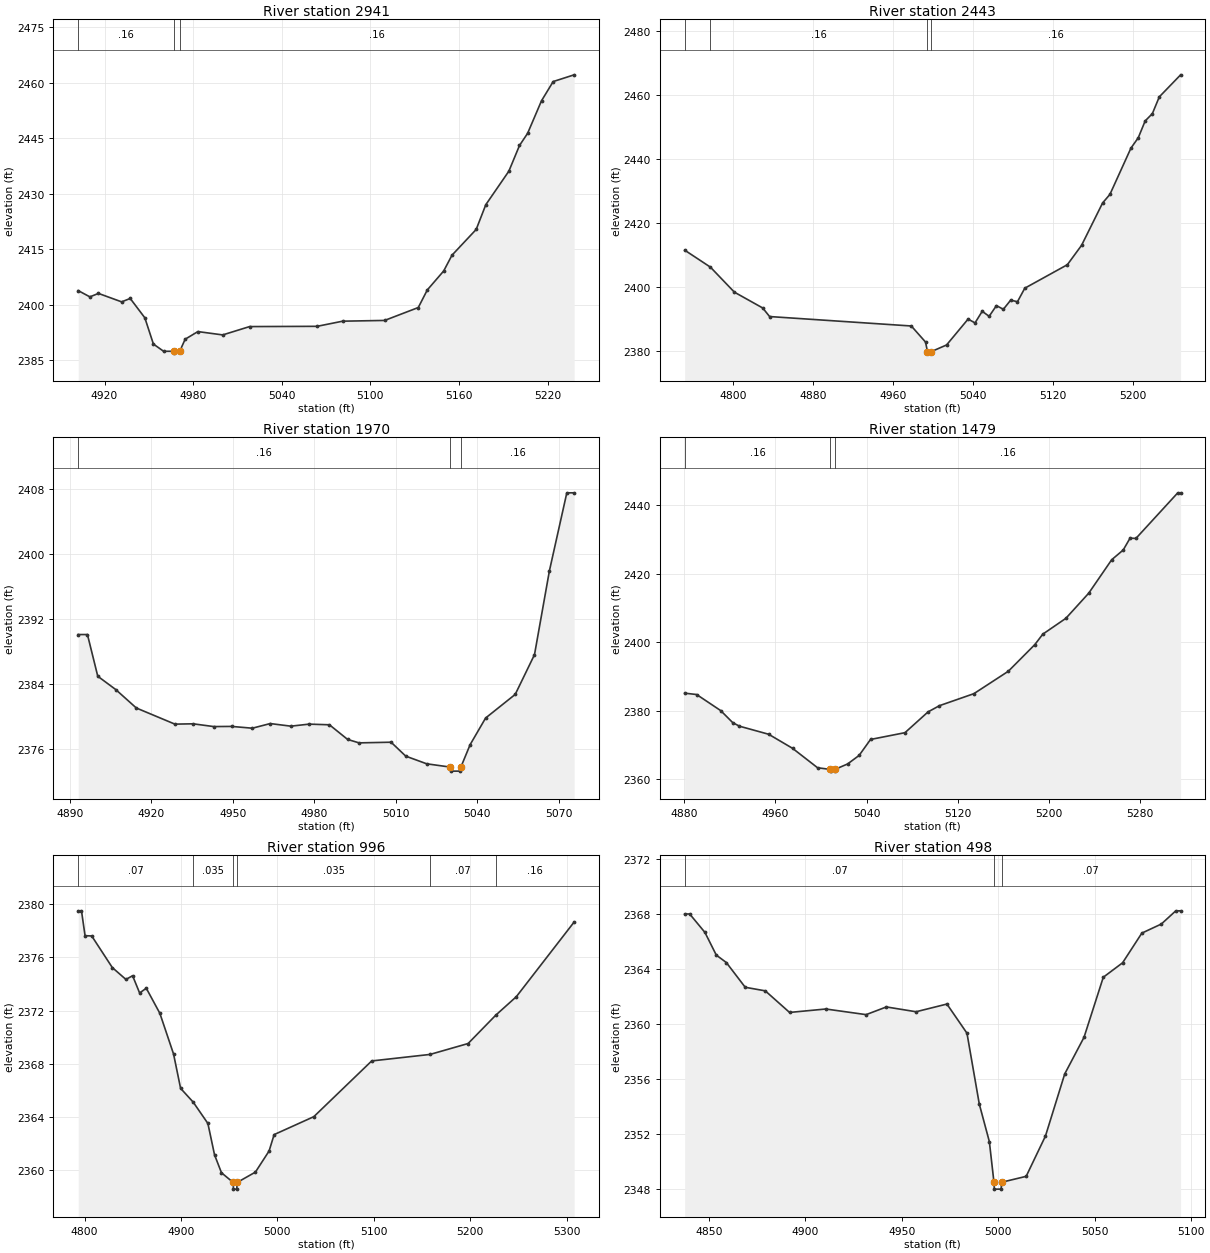
Type RM Length L Ch R = 1,2941,498,498,498
BEGIN DESCRIPTION:
Sweetwater Creek Trib 9 T 5.0
END DESCRIPTION:
XS GIS Cut Line= 3
      1365154.99      6809338.01      1365204.10      6809253.43
      1365305.00      6809037.99
#Sta/Elev= 30
  4902.2 2403.87  4910.1 2402.18  4915.9 2403.11  4931.6 2400.83  4937.4 2401.75
  4947.3 2396.52  4953.1 2389.43  4960.0 2387.48  4966.9 2387.48  4967.1 2386.98
  4970.9 2387.48  4974.6 2390.74  4983.2 2392.80  5000.0 2391.90  5018.2 2394.15
  5063.9 2394.22  5081.2 2395.61  5109.6 2395.81  5132.4 2399.30  5138.5 2404.05
  5149.6 2409.18  5155.2 2413.43  5171.6 2420.40  5178.1 2427.08  5193.7 2436.13
  5200.9 2443.07  5206.4 2446.36  5215.8 2455.15  5223.7 2460.34  5237.9 2462.16
#Mann=3,-1,0
  4902.2    0.16       0  4966.9    0.07       0  4970.9    0.16       0
Bank Sta=4966.9,4970.9
Exp/Cntr=0.3,0.1

Type RM Length L Ch R = 1,2443,473,473,473
BEGIN DESCRIPTION:
Sweetwater Creek Trib 9 T 4.0
END DESCRIPTION:
XS GIS Cut Line= 3
      1365355.00      6809588.00      1365525.42      6809407.83
      1365705.02      6809237.98
#Sta/Elev= 30
  4752.0 2411.66  4777.7 2406.35  4801.6 2398.54  4829.9 2393.59  4836.8 2390.91
  4978.3 2387.96  4992.5 2382.94  4994.4 2379.98  4994.7 2379.48  4998.4 2379.98
  5013.5 2382.03  5035.0 2390.12  5041.9 2388.92  5049.1 2392.56  5056.0 2390.98
  5063.3 2394.33  5070.2 2393.18  5077.5 2396.03  5084.3 2395.55  5091.6 2399.77
  5134.1 2407.11  5148.3 2413.17  5169.3 2426.41  5176.6 2429.08  5197.6 2443.55
  5204.9 2446.78  5211.8 2452.04  5219.0 2454.33  5225.9 2459.56  5247.2 2466.45
#Mann=4,-1,0
  4752.0    0.07       0  4777.7    0.16       0  4994.4    0.07       0
  4998.4    0.16       0
Bank Sta=4994.4,4998.4
Exp/Cntr=0.3,0.1

Type RM Length L Ch R = 1,1970,491,491,491
BEGIN DESCRIPTION:
Sweetwater Creek Trib 9 T 3.0
END DESCRIPTION:
XS GIS Cut Line= 3
      1365754.97      6809688.03      1365835.28      6809617.48
      1365905.00      6809588.00
#Sta/Elev= 30
  4893.1 2390.08  4896.5 2390.08  4900.3 2384.96  4906.9 2383.33  4914.5 2381.06
  4928.7 2379.08  4935.4 2379.12  4943.0 2378.78  4949.6 2378.80  4957.2 2378.58
  4963.8 2379.15  4971.4 2378.83  4978.1 2379.08  4985.6 2379.00  4992.3 2377.20
  4996.5 2376.78  5008.3 2376.86  5013.7 2375.15  5021.4 2374.21  5030.0 2373.81
  5030.3 2373.31  5033.8 2373.31  5034.0 2373.81  5037.4 2376.56  5043.1 2379.83
  5054.0 2382.73  5061.1 2387.61  5066.6 2397.92  5073.0 2407.48  5075.7 2407.48
#Mann=3,-1,0
  4893.1    0.16       0  5030.0    0.07       0  5034.0    0.16       0
Bank Sta=5030,5034
Exp/Cntr=0.3,0.1

Type RM Length L Ch R = 1,1479,483,483,483
BEGIN DESCRIPTION:
Sweetwater Creek Trib 9 T 2.0
END DESCRIPTION:
XS GIS Cut Line= 3
      1366004.98      6810038.01      1366118.58      6810001.23
      1366154.99      6809688.04
#Sta/Elev= 30
  4880.6 2385.16  4891.1 2384.76  4912.2 2380.07  4922.7 2376.57  4928.6 2375.53
  4954.2 2373.18  4975.2 2369.07  4997.1 2363.41  5008.3 2362.93  5008.6 2362.43
  5012.1 2362.43  5012.3 2362.93  5023.4 2364.52  5033.5 2367.01  5043.5 2371.66
  5073.7 2373.64  5093.9 2379.69  5103.9 2381.51  5134.1 2385.01  5164.3 2391.55
  5187.5 2399.31  5194.5 2402.36  5214.7 2406.97  5234.8 2414.32  5254.9 2424.06
  5265.0 2426.90  5271.0 2430.36  5276.1 2430.26  5312.8 2443.56  5315.3 2443.56
#Mann=3,-1,0
  4880.6    0.16       0  5008.3    0.07       0  5012.3    0.16       0
Bank Sta=5008.3,5012.3
Exp/Cntr=0.3,0.1

Type RM Length L Ch R = 1,996,498,498,498
BEGIN DESCRIPTION:
Sweetwater Creek Trib 9 T 1.0
END DESCRIPTION:
XS GIS Cut Line= 3
      1366255.01      6810437.99      1366404.90      6810295.81
      1366405.00      6809988.01
#Sta/Elev= 30
  4793.4 2379.50  4796.8 2379.50  4800.5 2377.63  4807.4 2377.61  4828.8 2375.23
  4842.9 2374.34  4849.8 2374.62  4857.1 2373.32  4864.0 2373.68  4878.1 2371.79
  4892.3 2368.73  4899.6 2366.15  4912.7 2365.11  4927.9 2363.51  4934.8 2361.15
  4942.0 2359.80  4954.2 2359.07  4954.4 2358.57  4957.9 2358.57  4958.2 2359.07
  4977.2 2359.85  4991.4 2361.44  4996.6 2362.67  5037.8 2364.02  5097.8 2368.21
  5158.3 2368.70  5197.8 2369.52  5226.6 2371.66  5247.8 2373.04  5307.8 2378.66
#Mann=6,-1,0
  4793.4    0.07       0  4912.7   0.035       0  4954.2   0.035       0
  4958.2   0.035       0  5158.3    0.07       0  5226.6    0.16       0
Bank Sta=4954.2,4958.2
Exp/Cntr=0.3,0.1

Type RM Length L Ch R = 1,498,109,109,109
BEGIN DESCRIPTION:
Sweetwater Creek Trib 9 T 2519
END DESCRIPTION:
XS GIS Cut Line= 3
      1366805.00      6810588.01      1366852.55      6810432.52
      1366855.00      6810337.96
#Sta/Elev= 30
  4837.4 2367.99  4840.0 2367.99  4847.9 2366.65  4853.8 2365.00  4859.0 2364.46
  4868.8 2362.66  4879.2 2362.40  4891.8 2360.83  4910.6 2361.08  4931.5 2360.67
  4942.0 2361.23  4957.4 2360.88  4973.4 2361.44  4983.8 2359.32  4990.2 2354.16
  4995.4 2351.44  4997.8 2348.48  4998.0 2347.98  5001.5 2347.98  5001.8 2348.48
  5014.5 2348.91  5024.5 2351.84  5034.5 2356.36  5044.5 2359.02  5054.5 2363.39
  5064.5 2364.44  5074.5 2366.60  5084.6 2367.26  5092.1 2368.22  5094.6 2368.22
#Mann=3,-1,0
  4837.4    0.07       0  4997.8    0.07       0  5001.8    0.07       0
Bank Sta=4997.8,5001.8
Exp/Cntr=0.3,0.1

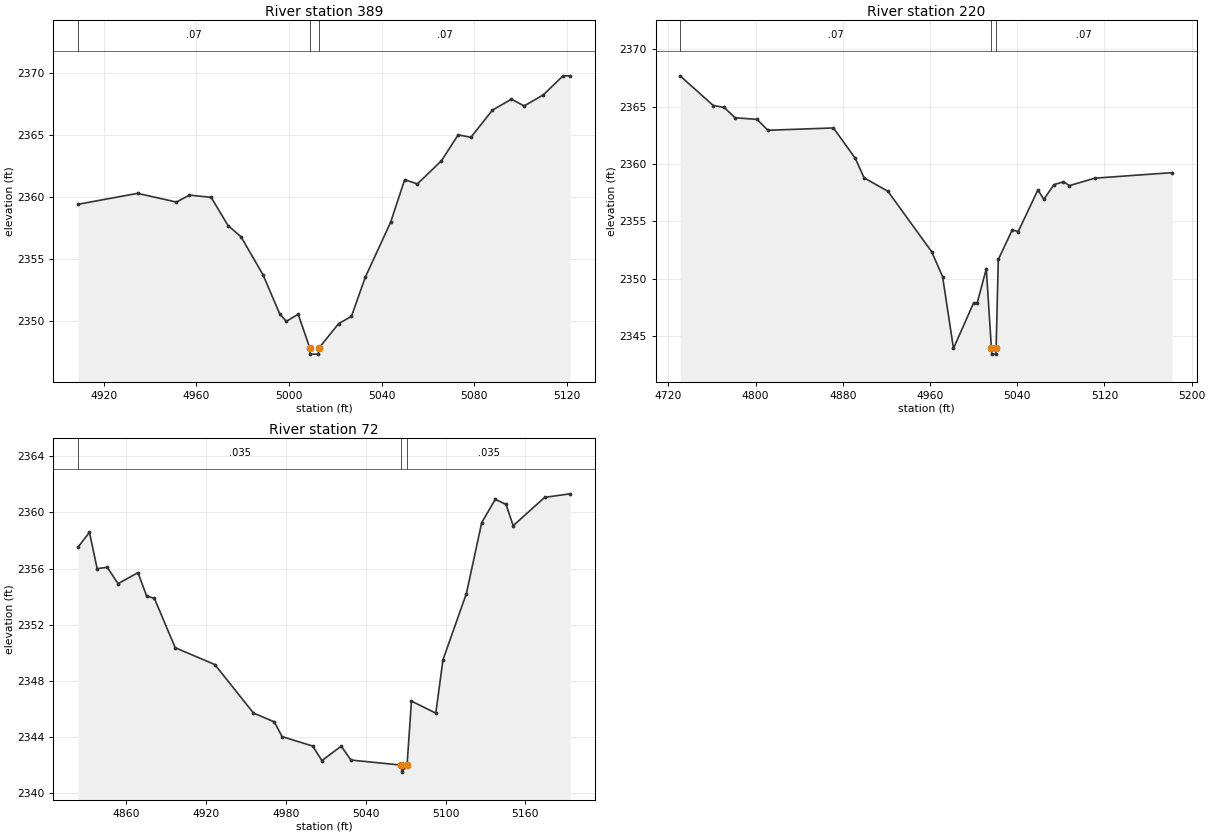
Type RM Length L Ch R = 1,389,169,169,169
BEGIN DESCRIPTION:
Sweetwater Creek Trib 9 T 4512
END DESCRIPTION:
XS GIS Cut Line= 3
      1366920.18      6810519.42      1366961.01      6810437.98
      1366910.63      6810327.53
#Sta/Elev= 30
  4908.9 2359.43  4934.6 2360.31  4951.4 2359.61  4957.0 2360.17  4966.4 2359.99
  4973.7 2357.72  4979.3 2356.82  4988.8 2353.76  4996.1 2350.58  4998.9 2350.01
  5004.0 2350.58  5009.0 2347.87  5009.2 2347.37  5012.7 2347.37  5013.0 2347.87
  5021.5 2349.83  5027.0 2350.41  5033.0 2353.57  5043.9 2357.97  5050.0 2361.41
  5055.5 2361.07  5065.9 2362.94  5073.1 2365.02  5078.6 2364.82  5087.9 2367.01
  5096.1 2367.89  5101.6 2367.35  5109.9 2368.24  5118.4 2369.77  5121.4 2369.77
#Mann=3,-1,0
  4908.9    0.07       0  5009.0    0.07       0  5013.0    0.07       0
Bank Sta=5009,5013
Exp/Cntr=0.3,0.1

Type RM Length L Ch R = 1,220,148,148,148
BEGIN DESCRIPTION:
Sweetwater Creek Trib 9 T 4405
END DESCRIPTION:
XS GIS Cut Line= 4
      1367128.94      6810207.64      1367114.93      6810476.47
      1367113.50      6810497.15      1366965.50      6810561.22
#Sta/Elev= 30
  4730.8 2367.70  4761.2 2365.11  4771.2 2364.94  4781.2 2364.04  4801.3 2363.90
  4811.3 2362.95  4871.4 2363.15  4891.4 2360.51  4899.5 2358.80  4921.4 2357.62
  4961.5 2352.35  4971.5 2350.18  4981.5 2343.91  5000.0 2347.89  5003.3 2347.89
  5011.6 2350.86  5016.3 2343.91  5016.6 2343.41  5020.3 2343.41  5020.6 2343.91
  5022.6 2351.67  5035.4 2354.25  5040.9 2354.11  5058.9 2357.74  5064.4 2356.92
  5073.6 2358.20  5082.4 2358.45  5087.9 2358.12  5111.3 2358.77  5182.0 2359.25
#Mann=3,-1,0
  4730.8    0.07       0  5016.3    0.07       0  5020.6    0.07       0
Bank Sta=5016.3,5020.6
Exp/Cntr=0.3,0.1

Type RM Length L Ch R = 1,72,0,0,0
BEGIN DESCRIPTION:
Sweetwater Creek Trib 9 T 4511
END DESCRIPTION:
XS GIS Cut Line= 3
      1367086.01      6810559.31      1367238.52      6810470.66
      1367416.72      6810395.26
#Sta/Elev= 30
  4823.6 2357.52  4832.2 2358.58  4838.0 2355.99  4845.6 2356.09  4853.7 2354.92
  4868.7 2355.71  4875.2 2354.04  4881.0 2353.88  4896.7 2350.36  4926.5 2349.16
  4955.5 2345.71  4971.2 2345.08  4977.0 2344.03  5000.0 2343.36  5007.0 2342.32
  5021.5 2343.35  5028.8 2342.36  5066.7 2342.00  5067.0 2341.50  5071.0 2342.00
  5074.3 2346.56  5092.6 2345.70  5098.0 2349.50  5115.6 2354.22  5127.1 2359.26
  5137.3 2360.93  5145.4 2360.57  5150.8 2359.05  5174.5 2361.07  5193.5 2361.32
#Mann=3,-1,0
  4823.6   0.035       0  5066.7   0.035       0  5071.0   0.035       0
Bank Sta=5066.7,5071
Exp/Cntr=0.3,0.1

Chan Stop Cuts=-1