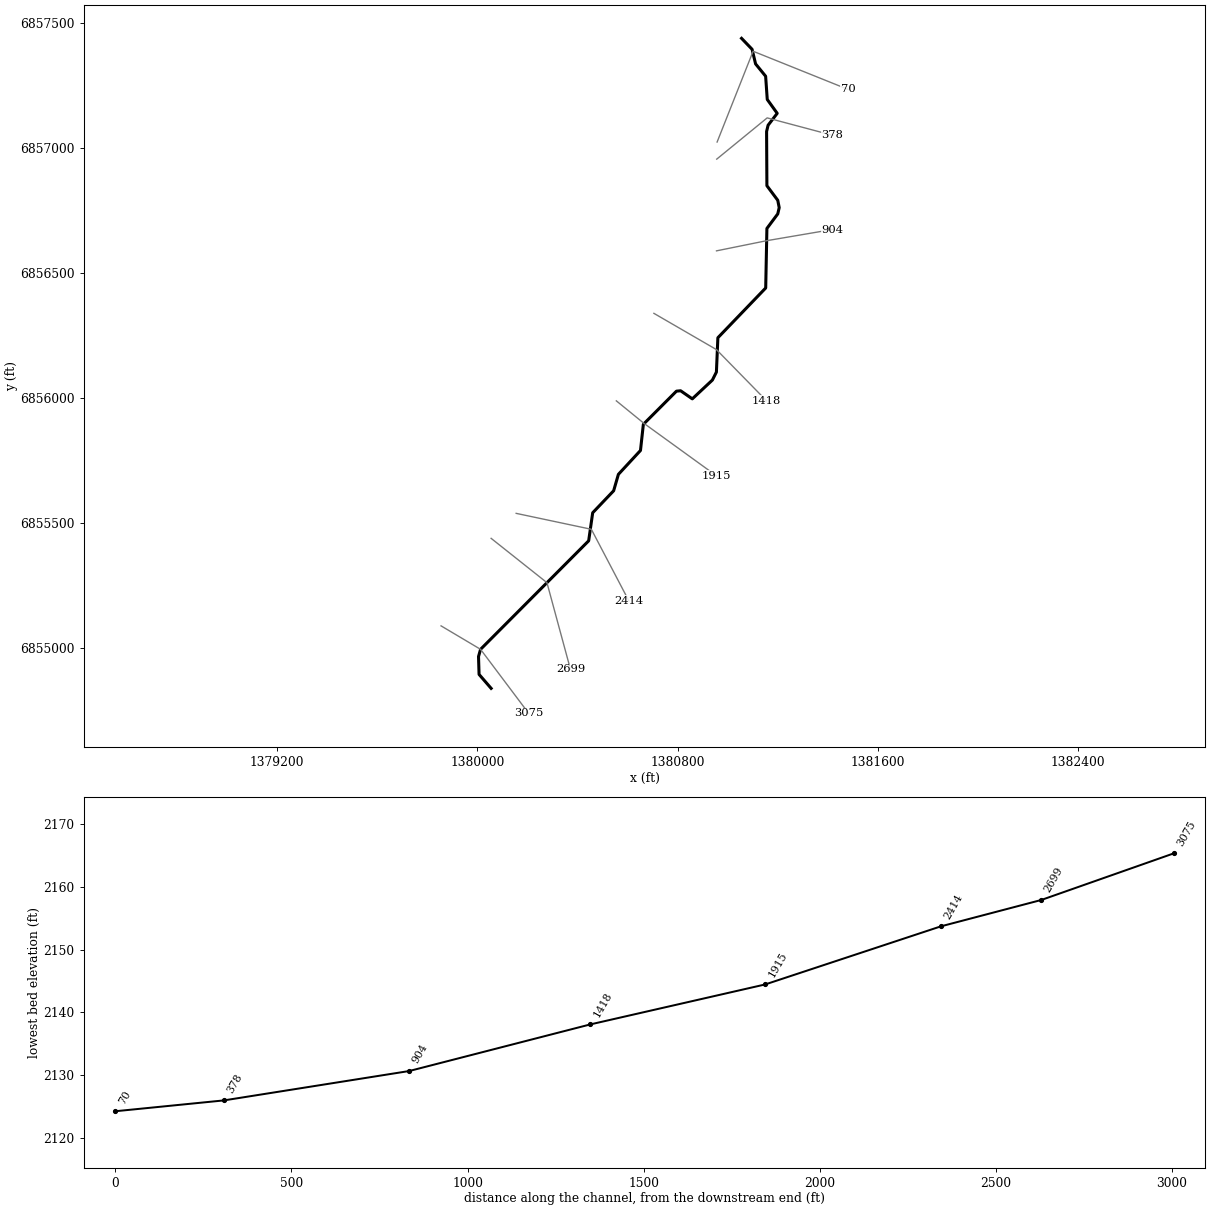
--- Town Creek Trib.prj (project) ---

Proj Title=Town Creek Trib Base Level Engineering
Current Plan=p01
Default Exp/Contr=0.3,0.1
English Units
Geom File=g01
Flow File=f01
Plan File=p01
Y Axis Title=Elevation
X Axis Title(PF)=Main Channel Distance
X Axis Title(XS)=Station
BEGIN DESCRIPTION:
Town Creek Trib
END DESCRIPTION:
DSS Export Rating Curves= 0
DSS Export Rating Curve Sorted= 0
DSS Export Volume Flow Curves= 0
DXF OffsetX= 0
DXF OffsetY= 0
DXF ScaleX= 1
DXF ScaleY= 10

--- Town Creek Trib.p01 (plan) ---

Plan Title=Multiple Run
Short Identifier=Multiple
Geom File=g01
Flow File=f01
Subcritical Flow
K Sum by GR= 0
Std Step Tol= 0.01
Critical Tol= 0.01
Num of Std Step Trials= 20
Max Error Tol= 0.3
Flow Tol Ratio= 0.001
Split Flow NTrial= 30
Split Flow Tol= 0.02
Split Flow Ratio= 0.02
Log Output Level= 0
Friction Slope Method= 1
Unsteady Friction Slope Method= 2
Unsteady Bridges Friction Slope Method= 1
Parabolic Critical Depth
Global Vel Dist=  1 , 1 , 1
Global Log Level= 0
CheckData=True
Encroach Param= -1, 0, 0, 0
BEGIN DESCRIPTION:
Multiple Run
END DESCRIPTION:

--- Town Creek Trib.f01 (steady flow) ---

Flow Title=Multiple
Number of Profiles=7
Profile Names=10-year,25-year,50-year,1pct_min,100-year,1pct_plu,500-year
River Rch & RM= Town Creek Trib,Reach-1,3075
      93     123     148      88     176     351     253
Boundary for River Rch & Prof#=Town Creek Trib,Reach-1,1
Up Type=0
Dn Type=3
Dn Slope=0.005
Boundary for River Rch & Prof#=Town Creek Trib,Reach-1,2
Up Type=0
Dn Type=3
Dn Slope=0.005
Boundary for River Rch & Prof#=Town Creek Trib,Reach-1,3
Up Type=0
Dn Type=3
Dn Slope=0.005
Boundary for River Rch & Prof#=Town Creek Trib,Reach-1,4
Up Type=0
Dn Type=3
Dn Slope=0.005
Boundary for River Rch & Prof#=Town Creek Trib,Reach-1,5
Up Type=0
Dn Type=3
Dn Slope=0.005
Boundary for River Rch & Prof#=Town Creek Trib,Reach-1,6
Up Type=0
Dn Type=3
Dn Slope=0.005
Boundary for River Rch & Prof#=Town Creek Trib,Reach-1,7
Up Type=0
Dn Type=3
Dn Slope=0.005

--- Town Creek Trib.g01 (geometry) ---

Geom Title=Existing Conditions

River Reach=Town Creek Trib,Reach-1
Reach XY= 30
      1380055.00      6854838.00      1380006.77      6854893.84
      1380004.60      6854965.30      1380012.76      6854994.18
      1380444.48      6855428.21      1380460.54      6855540.42
      1380544.20      6855628.33      1380563.18      6855694.04
      1380651.37      6855789.50      1380662.86      6855894.17
      1380795.00      6856026.76      1380811.67      6856028.38
      1380858.35      6855996.00      1380938.57      6856071.17
      1380954.60      6856103.15      1380960.47      6856240.45
      1381151.46      6856439.46      1381156.24      6856677.50
      1381199.62      6856735.82      1381205.38      6856760.81
      1381199.62      6856790.18      1381156.24      6856848.50
      1381155.01      6857065.35      1381161.02      6857090.45
      1381197.44      6857138.00      1381157.67      6857193.49
      1381151.19      6857286.42      1381111.03      6857335.78
      1381097.09      6857394.15      1381055.00      6857438.00

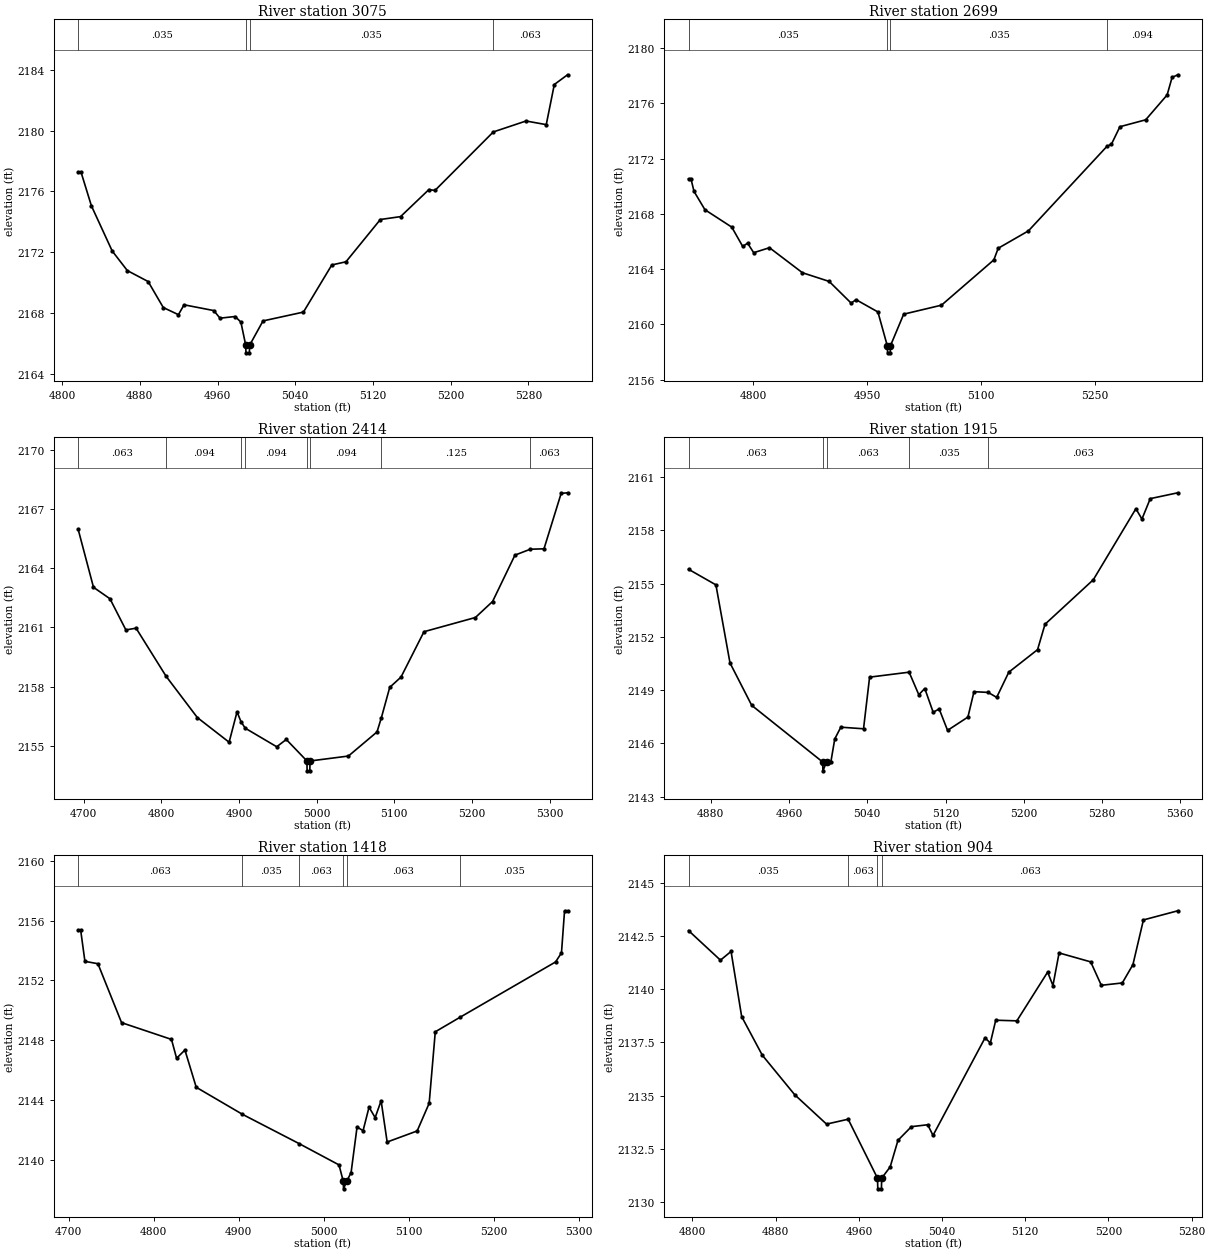
Type RM Length L Ch R = 1,3075,376,376,376
BEGIN DESCRIPTION:
Town Creek Trib 6.0
END DESCRIPTION:
XS GIS Cut Line= 3
      1379855.04      6855087.98      1380012.76      6854994.18
      1380205.01      6854737.99
#Sta/Elev= 30
  4816.5 2177.27  4819.4 2177.27  4830.1 2175.05  4851.5 2172.08  4867.1 2170.79
  4888.5 2170.07  4904.1 2168.36  4919.7 2167.89  4925.5 2168.54  4956.1 2168.16
  4962.5 2167.66  4978.1 2167.77  4984.0 2167.40  4989.0 2165.88  4989.2 2165.38
  4992.7 2165.38  4993.0 2165.88  5006.8 2167.48  5048.4 2168.06  5077.6 2171.16
  5092.2 2171.37  5127.6 2174.15  5148.4 2174.34  5177.6 2176.12  5183.8 2176.06
  5243.9 2179.91  5277.6 2180.63  5298.4 2180.39  5306.7 2183.03  5320.3 2183.67
#Mann=4,-1,0
  4816.5   0.035       0  4989.0   0.035       0  4993.0   0.035       0
  5243.9   0.063       0
Bank Sta=4989,4993
Exp/Cntr=0.3,0.1

Type RM Length L Ch R = 1,2699,285,285,285
BEGIN DESCRIPTION:
Town Creek Trib 5.0
END DESCRIPTION:
XS GIS Cut Line= 3
      1380054.99      6855438.01      1380277.84      6855260.83
      1380371.65      6854914.41
#Sta/Elev= 30
  4715.3 2170.54  4718.5 2170.54  4722.5 2169.63  4736.9 2168.30  4772.2 2167.04
  4786.6 2165.64  4793.0 2165.88  4801.0 2165.19  4821.8 2165.55  4865.1 2163.74
  4900.3 2163.11  4929.2 2161.54  4935.6 2161.79  4964.4 2160.90  4976.8 2158.44
  4977.1 2157.94  4980.6 2157.94  4980.8 2158.44  4998.3 2160.74  5048.0 2161.39
  5116.9 2164.67  5122.6 2165.51  5162.4 2166.77  5265.5 2172.88  5271.6 2173.05
  5282.7 2174.31  5316.6 2174.81  5344.8 2176.61  5351.3 2177.88  5358.9 2178.07
#Mann=4,-1,0
  4715.3   0.035       0  4976.8   0.035       0  4980.8   0.035       0
  5265.5   0.094       0
Bank Sta=4976.8,4980.8
Exp/Cntr=0.3,0.1

Type RM Length L Ch R = 1,2414,499,499,499
BEGIN DESCRIPTION:
Town Creek Trib 4.0
END DESCRIPTION:
XS GIS Cut Line= 3
      1380154.98      6855538.00      1380455.19      6855474.29
      1380604.99      6855188.01
#Sta/Elev= 30
  4693.1 2165.96  4712.8 2163.03  4734.0 2162.45  4754.5 2160.87  4767.6 2160.96
  4806.3 2158.52  4846.5 2156.43  4887.4 2155.18  4897.6 2156.72  4902.8 2156.21
  4908.2 2155.89  4948.7 2154.95  4961.0 2155.32  4987.6 2154.23  4987.8 2153.73
  4991.3 2153.73  4991.6 2154.23  5041.0 2154.48  5077.8 2155.70  5083.5 2156.43
  5094.2 2157.96  5108.7 2158.48  5138.3 2160.78  5204.5 2161.50  5226.6 2162.31
  5255.4 2164.66  5275.2 2164.96  5292.8 2164.98  5314.9 2167.79  5323.1 2167.82
#Mann=8,-1,0
  4693.1   0.063       0  4806.3   0.094       0  4902.8   0.063       0
  4908.2   0.094       0  4987.6    0.07       0  4991.6   0.094       0
  5083.5   0.125       0  5275.2   0.063       0
Bank Sta=4987.6,4991.6
Exp/Cntr=0.3,0.1

Type RM Length L Ch R = 1,1915,497,497,497
BEGIN DESCRIPTION:
Town Creek Trib 3.0
END DESCRIPTION:
XS GIS Cut Line= 3
      1380554.97      6855988.02      1380665.52      6855897.79
      1380955.00      6855688.00
#Sta/Elev= 30
  4857.3 2155.81  4885.3 2154.93  4899.7 2150.53  4921.9 2148.14  4994.4 2144.95
  4994.7 2144.45  4998.4 2144.95  5002.8 2144.95  5006.8 2146.25  5013.0 2146.91
  5036.2 2146.82  5042.4 2149.73  5082.8 2150.01  5092.7 2148.74  5098.8 2149.09
  5107.4 2147.75  5113.5 2147.94  5122.1 2146.73  5142.9 2147.48  5149.1 2148.91
  5163.6 2148.87  5172.3 2148.59  5184.7 2150.01  5214.1 2151.28  5221.7 2152.71
  5271.1 2155.22  5314.6 2159.22  5320.8 2158.64  5329.3 2159.79  5357.5 2160.12
#Mann=5,-1,0
  4857.3   0.063       0  4994.4   0.063       0  4998.4   0.063       0
  5082.8   0.035       0  5163.6   0.063       0
Bank Sta=4994.4,4998.4
Exp/Cntr=0.3,0.1

Type RM Length L Ch R = 1,1418,514,514,514
BEGIN DESCRIPTION:
Town Creek Trib 2.0
END DESCRIPTION:
XS GIS Cut Line= 3
      1380704.97      6856338.02      1380954.58      6856193.17
      1381154.99      6855988.01
#Sta/Elev= 30
  4711.4 2155.36  4714.3 2155.36  4719.3 2153.27  4734.6 2153.11  4762.4 2149.17
  4821.1 2148.05  4827.1 2146.79  4836.9 2147.34  4850.2 2144.85  4904.6 2143.04
  4971.3 2141.08  5018.1 2139.66  5023.1 2138.56  5023.4 2138.06  5027.1 2138.56
  5032.3 2139.15  5039.3 2142.19  5046.4 2141.95  5053.4 2143.52  5060.6 2142.82
  5067.6 2143.95  5074.7 2141.19  5110.0 2141.93  5124.1 2143.78  5131.3 2148.56
  5160.1 2149.52  5272.8 2153.23  5279.7 2153.84  5283.3 2156.65  5286.8 2156.65
#Mann=6,-1,0
  4711.4   0.063       0  4904.6   0.035       0  4971.3   0.063       0
  5023.1   0.063       0  5027.1   0.063       0  5160.1   0.035       0
Bank Sta=5023.1,5027.1
Exp/Cntr=0.3,0.1

Type RM Length L Ch R = 1,904,526,526,526
BEGIN DESCRIPTION:
Town Creek Trib 1.0
END DESCRIPTION:
XS GIS Cut Line= 3
      1380954.95      6856587.99      1381154.69      6856628.50
      1381417.59      6856673.32
#Sta/Elev= 30
  4796.2 2142.75  4826.9 2141.36  4837.1 2141.77  4847.3 2138.71  4867.1 2136.90
  4898.3 2135.04  4928.9 2133.66  4949.7 2133.89  4977.9 2131.12  4978.2 2130.62
  4981.7 2130.62  4981.9 2131.12  4990.1 2131.65  4997.6 2132.90  5010.5 2133.54
  5026.2 2133.63  5031.3 2133.13  5081.3 2137.71  5086.4 2137.47  5091.6 2138.54
  5111.9 2138.51  5141.5 2140.80  5146.6 2140.17  5152.5 2141.70  5182.9 2141.28
  5193.1 2140.18  5213.3 2140.29  5223.5 2141.15  5233.6 2143.25  5266.7 2143.68
#Mann=4,-1,0
  4796.2   0.035       0  4949.7   0.063       0  4977.9   0.063       0
  4981.9   0.063       0
Bank Sta=4977.9,4981.9
Exp/Cntr=0.3,0.1

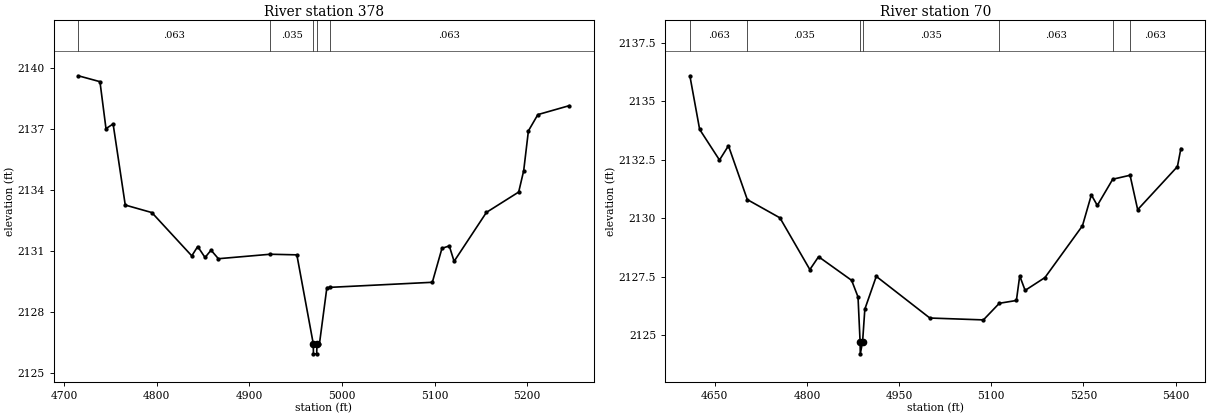
Type RM Length L Ch R = 1,378,308,308,308
BEGIN DESCRIPTION:
Town Creek Trib 0.1
END DESCRIPTION:
XS GIS Cut Line= 3
      1380955.93      6856954.87      1381157.34      6857119.82
      1381417.80      6857050.37
#Sta/Elev= 30
  4715.4 2139.61  4738.8 2139.32  4745.3 2137.01  4753.0 2137.24  4766.1 2133.25
  4794.8 2132.88  4837.9 2130.75  4844.3 2131.21  4852.2 2130.67  4858.7 2131.03
  4866.6 2130.61  4922.6 2130.83  4951.3 2130.80  4969.0 2126.43  4969.2 2125.93
  4972.7 2125.93  4973.0 2126.43  4975.7 2126.43  4983.7 2129.19  4986.7 2129.20
  5097.5 2129.45  5107.9 2131.12  5115.8 2131.24  5121.0 2130.48  5155.9 2132.89
  5190.7 2133.89  5196.1 2134.94  5201.2 2136.90  5211.4 2137.70  5245.3 2138.14
#Mann=5,-1,0
  4715.4   0.063       0  4922.6   0.035       0  4969.0   0.063       0
  4973.0   0.035       0  4986.7   0.063       0
Bank Sta=4969,4973
Exp/Cntr=0.3,0.1

Type RM Length L Ch R = 1,70,0,0,0
BEGIN DESCRIPTION:
Town Creek Trib 4406
END DESCRIPTION:
XS GIS Cut Line= 3
      1380957.41      6857023.20      1381101.13      6857386.40
      1381480.17      6857233.79
#Sta/Elev= 30
  4609.4 2136.08  4625.3 2133.79  4657.6 2132.48  4672.2 2133.09  4702.9 2130.79
  4756.0 2130.01  4804.7 2127.80  4818.9 2128.35  4872.7 2127.34  4883.1 2126.63
  4886.5 2124.70  4886.8 2124.20  4890.5 2124.70  4894.2 2126.11  4912.8 2127.51
  5000.0 2125.73  5087.2 2125.65  5113.1 2126.36  5140.9 2126.48  5146.3 2127.53
  5155.1 2126.91  5187.4 2127.46  5248.4 2129.67  5262.9 2130.99  5272.6 2130.54
  5297.7 2131.66  5325.9 2131.83  5338.3 2130.36  5403.0 2132.20  5408.6 2132.97
#Mann=7,-1,0
  4609.4   0.063       0  4702.9   0.035       0  4886.5   0.035       0
  4890.5   0.035       0  5113.1   0.063       0  5297.7   0.094       0
  5325.9   0.063       0
Bank Sta=4886.5,4890.5
Exp/Cntr=0.3,0.1

Chan Stop Cuts=-1