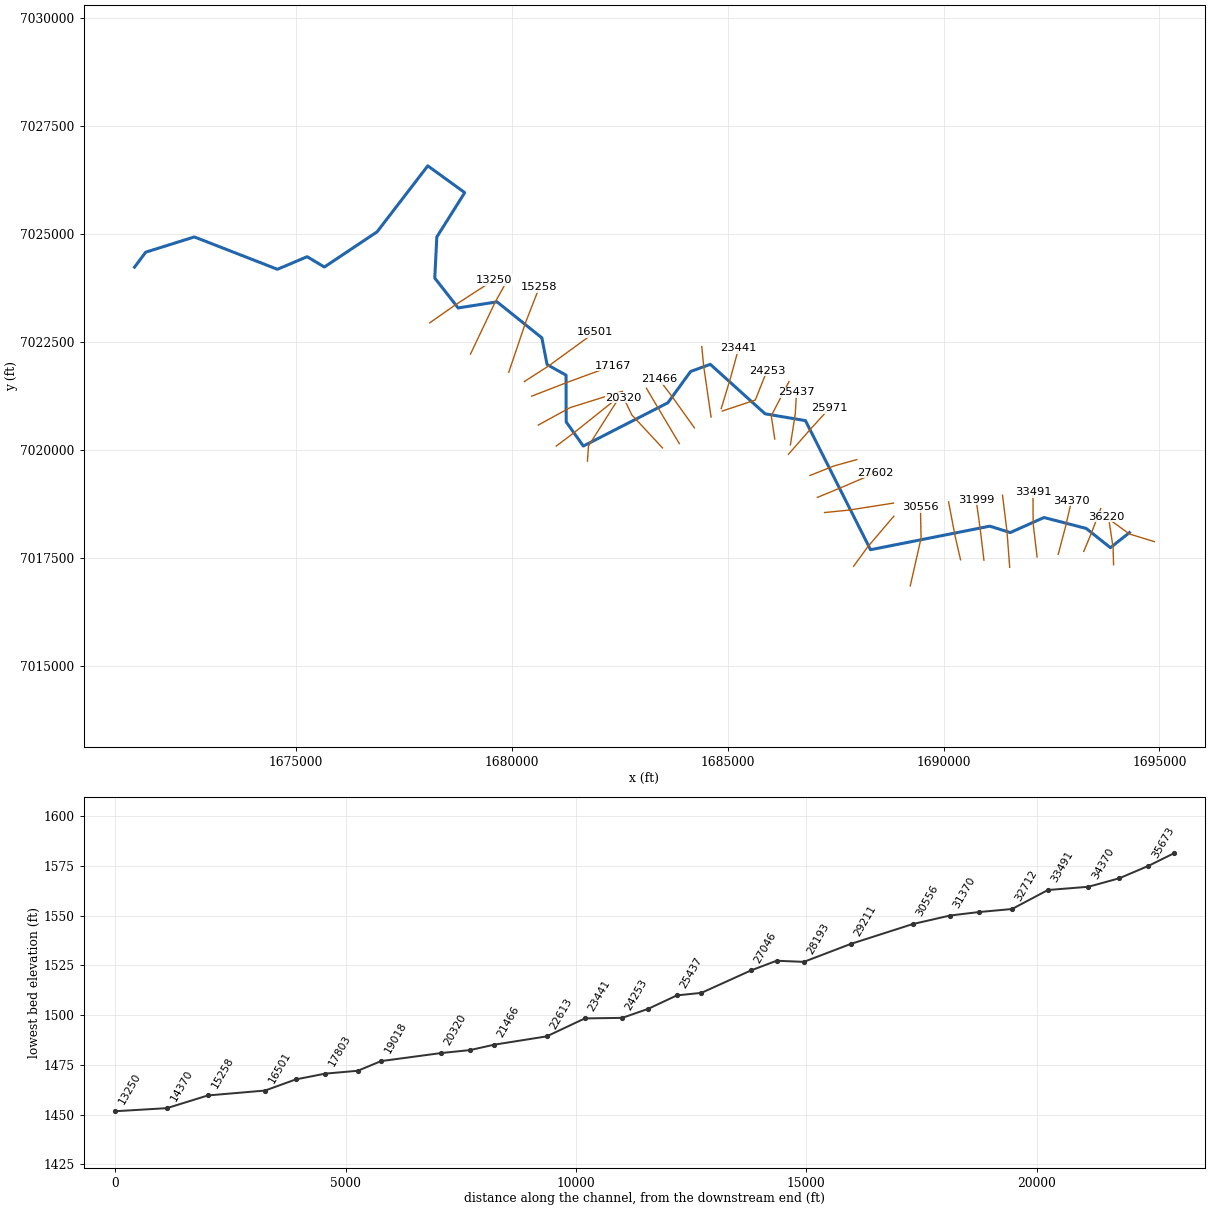
--- Antelope Creek.prj (project) ---

Proj Title=Antelope Creek Base Level Engineering
Current Plan=p01
Default Exp/Contr=0.3,0.1
English Units
Geom File=g01
Flow File=f01
Plan File=p01
BEGIN DESCRIPTION:
Antelope Creek
END DESCRIPTION:

--- Antelope Creek.p01 (plan) ---

Plan Title=Multiple Run
Short Identifier=Multiple
Geom File=g01
Flow File=f01
Subcritical Flow
K Sum by GR= 0
Std Step Tol= 0.01
Critical Tol= 0.01
Num of Std Step Trials= 20
Max Error Tol= 0.3
Flow Tol Ratio= 0.001
Split Flow NTrial= 30
Split Flow Tol= 0.02
Split Flow Ratio= 0.02
Log Output Level= 0
Friction Slope Method= 1
Unsteady Friction Slope Method= 2
Unsteady Bridges Friction Slope Method= 1
Parabolic Critical Depth
Global Vel Dist=  1 , 1 , 1
Global Log Level= 0
CheckData=True
Encroach Param= -1, 0, 0, 0
BEGIN DESCRIPTION:
Multiple Run
END DESCRIPTION:

--- Antelope Creek.f01 (steady flow) ---

Flow Title=Multiple
Number of Profiles=7
Profile Names=10-year,25-year,50-year,1pct_min,100-year,1pct_plu,500-year
River Rch & RM= Antelope Creek,Reach-1,36220
     248     343     420     257     514    1025     775
River Rch & RM= Antelope Creek,Reach-1,35673
     531     765     966     607    1211    2416    1926
River Rch & RM= Antelope Creek,Reach-1,29211
     604     874    1107     697    1390    2774    2222
River Rch & RM= Antelope Creek,Reach-1,25971
     862    1267    1623    1032    2060    4109    3360
River Rch & RM= Antelope Creek,Reach-1,24253
    1584    2373    3077    1977    3945    7871    6569
River Rch & RM= Antelope Creek,Reach-1,19018
    1661    2491    3233    2079    4148    8277    6920
River Rch & RM= Antelope Creek,Reach-1,17167
    1667    2498    3238    2080    4150    8281    6907
River Rch & RM= Antelope Creek,Reach-1,10120
    1813    2717    3524    2263    4516    9011    7515
River Rch & RM= Antelope Creek,Reach-1,4239
    1830    2743    3558    2286    4560    9099    7591
River Rch & RM= Antelope Creek,Reach-1,1361
    2102    3165    4118    2654    5294   10564    8863
Boundary for River Rch & Prof#=Antelope Creek,Reach-1,1
Up Type=0
Dn Type=3
Dn Slope=0.005
Boundary for River Rch & Prof#=Antelope Creek,Reach-1,2
Up Type=0
Dn Type=3
Dn Slope=0.005
Boundary for River Rch & Prof#=Antelope Creek,Reach-1,3
Up Type=0
Dn Type=3
Dn Slope=0.005
Boundary for River Rch & Prof#=Antelope Creek,Reach-1,4
Up Type=0
Dn Type=3
Dn Slope=0.005
Boundary for River Rch & Prof#=Antelope Creek,Reach-1,5
Up Type=0
Dn Type=3
Dn Slope=0.005
Boundary for River Rch & Prof#=Antelope Creek,Reach-1,6
Up Type=0
Dn Type=3
Dn Slope=0.005
Boundary for River Rch & Prof#=Antelope Creek,Reach-1,7
Up Type=0
Dn Type=3
Dn Slope=0.005

--- Antelope Creek.g01 (geometry) ---

Geom Title=Existing Conditions

River Reach=Antelope Creek,Reach-1
Reach XY= 30
      1694305.00      7018088.00      1693864.70      7017739.25
      1693303.74      7018184.52      1692325.03      7018437.96
      1691544.56      7018089.05      1691069.10      7018237.78
      1688306.46      7017691.54      1686799.41      7020682.39
      1685863.34      7020841.16      1684594.47      7021986.92
      1684138.25      7021821.54      1683611.21      7021095.80
      1681652.55      7020093.46      1681255.69      7020653.03
      1681251.39      7021736.50      1680812.85      7021981.81
      1680691.63      7022601.32      1679653.42      7023434.17
      1678752.57      7023293.52      1678210.82      7023985.69
      1678258.29      7024936.64      1678905.10      7025965.31
      1678049.13      7026585.95      1676875.47      7025057.63
      1675653.53      7024241.53      1675255.00      7024480.50
      1674565.55      7024189.10      1672641.19      7024938.42
      1671513.30      7024584.93      1671255.00      7024238.00

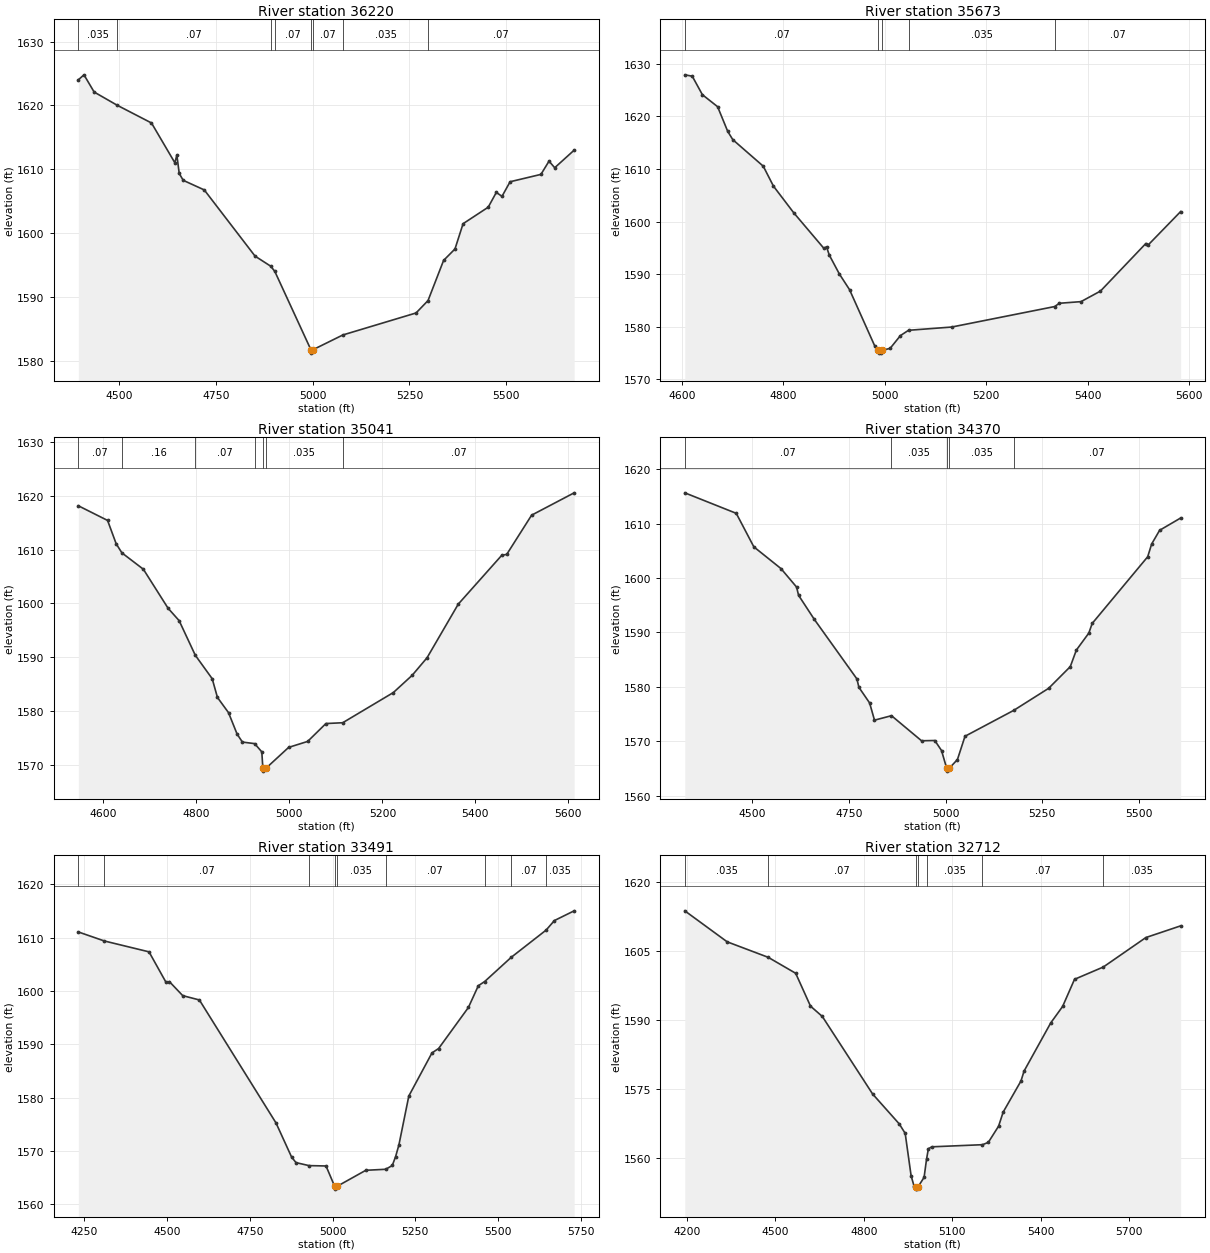
Type RM Length L Ch R = 1,36220,547,547,547
BEGIN DESCRIPTION:
Antelope Creek 67.0
END DESCRIPTION:
XS GIS Cut Line= 3
      1694884.06      7017878.78      1694305.54      7018055.81
      1693758.98      7018452.25
#Sta/Elev= 30
  4395.0 1624.01  4409.6 1624.79  4435.8 1622.10  4495.4 1620.03  4583.9 1617.26
  4644.2 1611.04  4649.4 1612.23  4655.5 1609.36  4665.9 1608.29  4720.2 1606.79
  4851.3 1596.44  4891.8 1594.86  4902.3 1594.05  4995.7 1581.77  4995.9 1581.27
  4999.7 1581.77  5078.0 1584.11  5267.0 1587.55  5297.9 1589.49  5338.1 1595.77
  5367.5 1597.56  5388.4 1601.51  5453.3 1604.09  5474.2 1606.40  5488.9 1605.79
  5509.8 1608.07  5589.4 1609.22  5610.3 1611.29  5625.0 1610.26  5675.2 1613.01
#Mann=8,-1,0
  4395.0   0.035       0  4495.4    0.07       0  4891.8   0.035       0
  4902.3    0.07       0  4995.7    0.07       0  4999.7    0.07       0
  5078.0   0.035       0  5297.9    0.07       0
Bank Sta=4995.7,4999.7
Exp/Cntr=0.3,0.1

Type RM Length L Ch R = 1,35673,632,632,632
BEGIN DESCRIPTION:
Mapping XS bd35294a
END DESCRIPTION:
XS GIS Cut Line= 3
      1693937.34      7017343.31      1693926.92      7017739.18
      1693840.31      7018314.28
#Sta/Elev= 30
  4605.7 1627.92  4620.4 1627.66  4640.4 1624.14  4670.4 1621.86  4690.4 1617.15
  4700.4 1615.59  4760.4 1610.55  4780.5 1606.76  4820.5 1601.69  4880.1 1594.91
  4885.1 1595.23  4890.5 1593.67  4910.5 1590.05  4930.5 1587.08  4980.5 1576.31
  4987.5 1575.51  4988.0 1575.01  4993.1 1575.01  4993.6 1575.51  5010.6 1575.92
  5030.9 1578.35  5046.8 1579.35  5132.0 1579.97  5334.7 1583.86  5344.4 1584.49
  5386.9 1584.80  5425.3 1586.81  5514.7 1595.85  5519.8 1595.62  5583.3 1601.92
#Mann=5,-1,0
  4605.7    0.07       0  4987.5    0.07       0  4993.6    0.07       0
  5046.8   0.035       0  5334.7    0.07       0
Bank Sta=4987.5,4993.6
Exp/Cntr=0.3,0.1

Type RM Length L Ch R = 1,35041,671,671,671
BEGIN DESCRIPTION:
Mapping XS 56c7f02e
END DESCRIPTION:
XS GIS Cut Line= 3
      1693246.94      7017652.21      1693421.42      7018071.48
      1693639.82      7018643.48
#Sta/Elev= 30
  4546.0 1618.19  4608.9 1615.46  4627.4 1611.11  4639.7 1609.42  4685.9 1606.37
  4739.0 1599.11  4762.8 1596.80  4797.6 1590.35  4833.9 1585.99  4845.2 1582.50
  4869.0 1579.67  4887.5 1575.67  4898.9 1574.19  4925.2 1573.90  4940.6 1572.37
  4942.9 1569.28  4943.4 1568.78  4949.1 1569.28  4998.3 1573.20  5039.2 1574.31
  5078.5 1577.64  5114.6 1577.79  5223.5 1583.41  5264.0 1586.62  5296.1 1589.90
  5363.1 1599.87  5456.7 1608.97  5467.4 1609.14  5520.9 1616.44  5612.4 1620.60
#Mann=7,-1,0
  4546.0    0.07       0  4639.7    0.16       0  4797.6    0.07       0
  4925.2   0.035       0  4942.9   0.035       0  4949.1   0.035       0
  5114.6    0.07       0
Bank Sta=4942.9,4949.1
Exp/Cntr=0.3,0.1

Type RM Length L Ch R = 1,34370,879,879,879
BEGIN DESCRIPTION:
Mapping XS 9de24ecc
END DESCRIPTION:
XS GIS Cut Line= 3
      1692655.80      7017585.38      1692829.41      7018245.09
      1692963.96      7018831.07
#Sta/Elev= 30
  4325.2 1615.66  4458.4 1611.89  4503.9 1605.73  4574.2 1601.73  4614.5 1598.34
  4619.7 1596.82  4660.0 1592.44  4770.7 1581.45  4775.8 1579.91  4803.6 1577.03
  4816.2 1573.87  4860.2 1574.69  4938.0 1570.08  4972.3 1570.13  4989.7 1568.29
  5003.1 1565.00  5003.6 1564.50  5009.4 1565.00  5030.9 1566.63  5050.5 1570.91
  5176.9 1575.68  5266.9 1579.72  5323.0 1583.71  5338.7 1586.75  5371.0 1589.88
  5379.7 1591.65  5523.4 1603.91  5533.6 1606.25  5554.2 1608.77  5608.6 1611.03
#Mann=5,-1,0
  4325.2    0.07       0  4860.2   0.035       0  5003.1   0.035       0
  5009.4   0.035       0  5176.9    0.07       0
Bank Sta=5003.1,5009.4
Exp/Cntr=0.3,0.1

Type RM Length L Ch R = 1,33491,779,779,779
BEGIN DESCRIPTION:
Mapping XS 7ef714bc
END DESCRIPTION:
XS GIS Cut Line= 3
      1692165.34      7017524.65      1692074.20      7018301.51
      1692069.86      7019017.61
#Sta/Elev= 30
  4231.9 1611.08  4310.4 1609.39  4445.5 1607.35  4497.1 1601.61  4507.1 1601.77
  4547.4 1599.14  4597.7 1598.33  4829.3 1575.27  4876.5 1568.86  4889.7 1567.84
  4928.8 1567.28  4980.4 1567.21  5006.6 1563.37  5007.1 1562.87  5013.1 1563.37
  5100.6 1566.40  5160.7 1566.59  5180.6 1567.30  5190.6 1568.96  5200.6 1571.15
  5230.6 1580.33  5300.6 1588.41  5320.6 1589.23  5410.6 1596.92  5440.6 1601.00
  5459.9 1601.79  5540.1 1606.33  5645.3 1611.42  5670.6 1613.22  5730.2 1615.04
#Mann=9,-1,0
  4231.9   0.035       0  4310.4    0.07       0  4928.8   0.035       0
  5006.6   0.035       0  5013.1   0.035       0  5160.7    0.07       0
  5459.9   0.035       0  5540.1    0.07       0  5645.3   0.035       0
Bank Sta=5006.6,5013.1
Exp/Cntr=0.3,0.1

Type RM Length L Ch R = 1,32712,713,713,713
BEGIN DESCRIPTION:
Mapping XS 700b32f0
END DESCRIPTION:
XS GIS Cut Line= 3
      1691531.09      7017283.23      1691468.58      7018109.67
      1691364.66      7018954.91
#Sta/Elev= 30
  4193.1 1613.83  4336.7 1607.09  4475.8 1603.72  4568.9 1600.25  4619.1 1593.11
  4659.2 1590.86  4829.7 1574.00  4919.9 1567.50  4940.0 1565.45  4960.1 1556.22
  4970.1 1553.97  4976.7 1553.82  4977.2 1553.32  4983.6 1553.82  5004.1 1555.88
  5012.3 1559.79  5018.6 1562.10  5030.3 1562.52  5201.9 1562.98  5221.7 1563.48
  5256.6 1567.01  5272.1 1570.07  5332.5 1576.84  5342.9 1578.99  5433.3 1589.46
  5473.6 1593.04  5513.9 1598.94  5611.4 1601.61  5755.7 1608.02  5873.5 1610.56
#Mann=7,-1,0
  4193.1   0.035       0  4475.8    0.07       0  4976.7    0.07       0
  4983.6    0.07       0  5012.3   0.035       0  5201.9    0.07       0
  5611.4   0.035       0
Bank Sta=4976.7,4983.6
Exp/Cntr=0.3,0.1

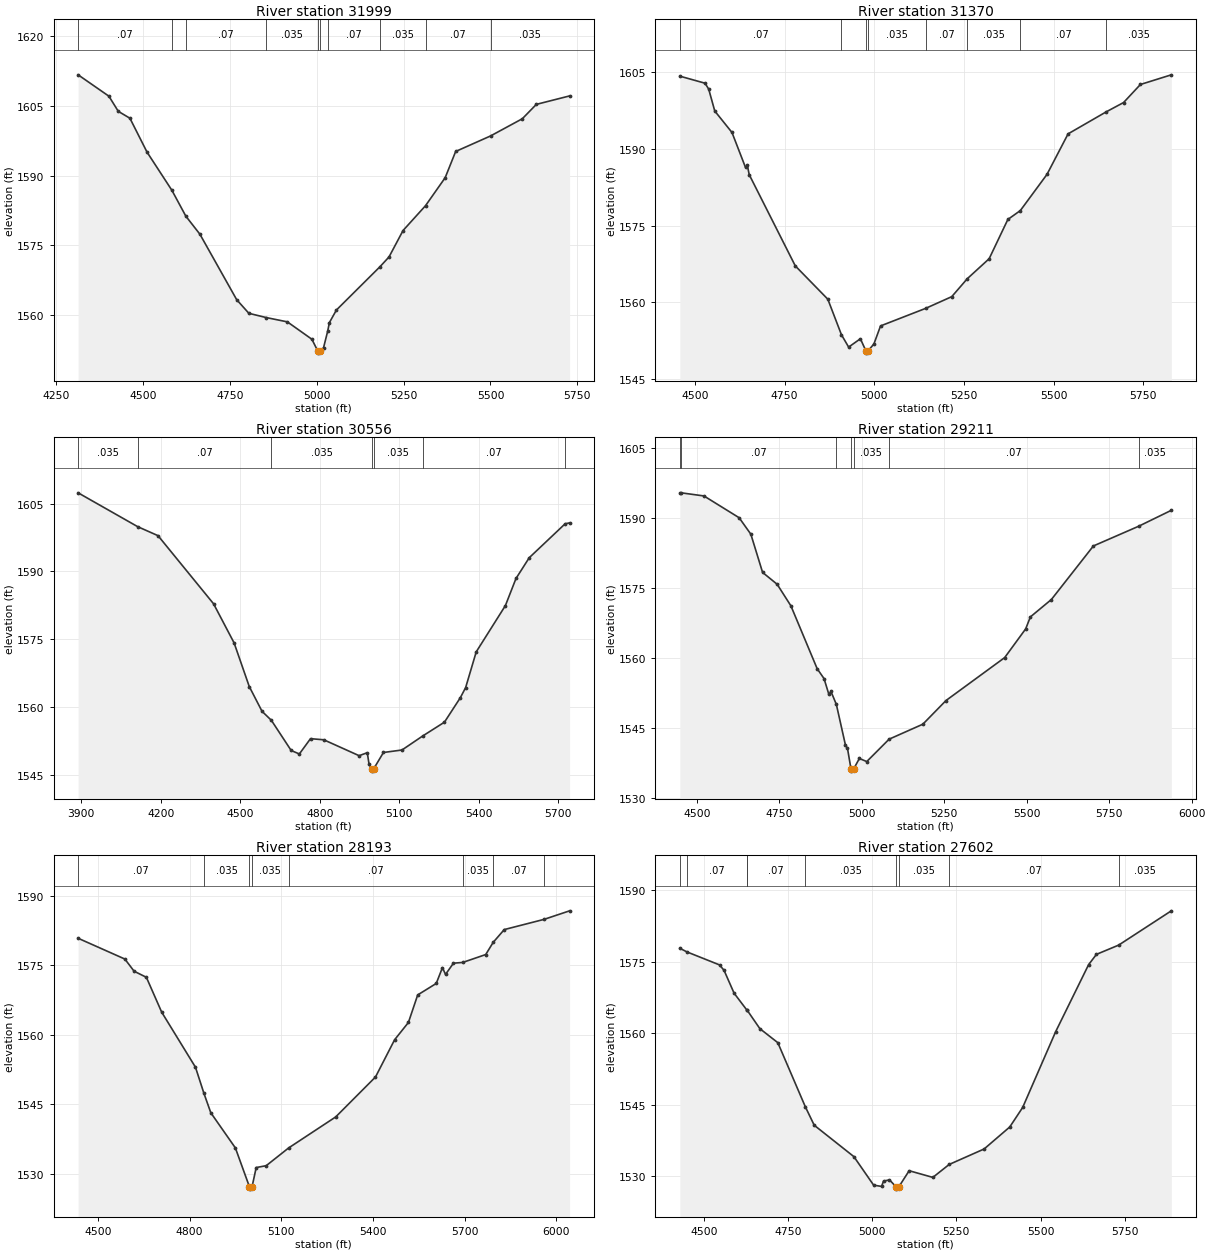
Type RM Length L Ch R = 1,31999,629,629,629
BEGIN DESCRIPTION:
Mapping XS 99ff0423
END DESCRIPTION:
XS GIS Cut Line= 3
      1690933.86      7017449.99      1690850.53      7018151.34
      1690753.30      7018852.75
#Sta/Elev= 30
  4313.3 1611.73  4401.9 1607.13  4428.9 1603.87  4462.4 1602.38  4511.6 1595.09
  4583.3 1586.85  4623.3 1581.30  4663.8 1577.41  4769.6 1563.32  4804.7 1560.38
  4853.9 1559.48  4915.5 1558.54  4986.0 1554.80  5002.7 1552.31  5003.2 1551.81
  5009.7 1552.31  5019.6 1552.98  5031.6 1556.57  5036.4 1558.38  5056.6 1561.09
  5182.2 1570.43  5208.0 1572.52  5248.4 1578.21  5313.0 1583.55  5369.6 1589.58
  5399.8 1595.23  5500.2 1598.57  5591.7 1602.28  5632.0 1605.37  5727.7 1607.19
#Mann=10,-1,0
  4313.3    0.07       0  4583.3    0.16       0  4623.3    0.07       0
  4853.9   0.035       0  5002.7   0.035       0  5009.7   0.035       0
  5031.6    0.07       0  5182.2   0.035       0  5313.0    0.07       0
  5500.2   0.035       0
Bank Sta=5002.7,5009.7
Exp/Cntr=0.3,0.1

Type RM Length L Ch R = 1,31370,814,814,814
BEGIN DESCRIPTION:
Mapping XS 0701ef61
END DESCRIPTION:
XS GIS Cut Line= 3
      1690392.19      7017459.51      1690266.33      7018006.37
      1690114.42      7018800.61
#Sta/Elev= 30
  4458.2 1604.25  4528.5 1602.87  4538.7 1601.71  4555.6 1597.43  4603.6 1593.23
  4641.3 1586.38  4646.4 1586.79  4651.6 1584.98  4780.0 1567.13  4870.7 1560.61
  4908.7 1553.65  4928.7 1551.24  4961.5 1552.87  4976.4 1550.56  4976.9 1550.06
  4983.5 1550.56  4999.2 1551.86  5017.6 1555.38  5143.1 1558.81  5216.1 1561.11
  5259.5 1564.63  5320.3 1568.53  5372.4 1576.21  5407.2 1577.95  5481.6 1585.04
  5540.3 1592.96  5646.9 1597.28  5695.0 1599.09  5741.9 1602.62  5828.0 1604.51
#Mann=8,-1,0
  4458.2    0.07       0  4908.7   0.035       0  4976.4   0.035       0
  4983.5   0.035       0  5143.1    0.07       0  5259.5   0.035       0
  5407.2    0.07       0  5646.9   0.035       0
Bank Sta=4976.4,4983.5
Exp/Cntr=0.3,0.1

Type RM Length L Ch R = 1,30556,1345,1345,1345
BEGIN DESCRIPTION:
Mapping XS 90d007fb
END DESCRIPTION:
XS GIS Cut Line= 3
      1689227.27      7016853.93      1689477.26      7017958.05
      1689463.38      7018680.25
#Sta/Elev= 30
  3888.2 1607.39  4112.8 1599.90  4189.7 1597.90  4399.3 1582.81  4476.8 1574.14
  4533.9 1564.49  4582.1 1559.00  4617.4 1557.00  4692.1 1550.32  4722.9 1549.55
  4765.0 1552.94  4815.2 1552.69  4948.4 1549.17  4979.2 1549.83  4985.9 1547.29
  4996.1 1546.25  4996.6 1545.75  5003.3 1546.25  5040.2 1549.88  5110.2 1550.43
  5188.2 1553.53  5270.3 1556.59  5330.3 1562.01  5350.3 1564.25  5390.3 1572.17
  5500.3 1582.41  5540.3 1588.42  5590.3 1593.02  5725.8 1600.54  5742.6 1600.73
#Mann=7,-1,0
  3888.2   0.035       0  4112.8    0.07       0  4617.4   0.035       0
  4996.1   0.035       0  5003.3   0.035       0  5188.2    0.07       0
  5725.8   0.035       0
Bank Sta=4996.1,5003.3
Exp/Cntr=0.3,0.1

Type RM Length L Ch R = 1,29211,1018,1018,1018
BEGIN DESCRIPTION:
Mapping XS cbf675e9
END DESCRIPTION:
XS GIS Cut Line= 3
      1687914.74      7017306.98      1688242.89      7017760.13
      1688847.07      7018468.48
#Sta/Elev= 30
  4447.8 1595.42  4452.0 1595.42  4521.0 1594.75  4627.7 1590.08  4663.2 1586.55
  4698.8 1578.36  4742.9 1575.82  4784.7 1571.19  4864.3 1557.72  4885.2 1555.59
  4899.9 1552.19  4906.1 1552.85  4922.5 1550.06  4950.2 1541.31  4956.3 1540.62
  4966.8 1536.26  4967.3 1535.76  4975.2 1536.26  4992.3 1538.47  5014.7 1537.81
  5082.5 1542.61  5184.8 1545.82  5255.1 1550.90  5433.0 1560.10  5496.7 1566.26
  5510.9 1568.82  5574.6 1572.55  5702.0 1584.03  5839.4 1588.26  5938.3 1591.67
#Mann=7,-1,0
  4447.8   0.035       0  4452.0    0.07       0  4922.5   0.035       0
  4966.8   0.035       0  4975.2   0.035       0  5082.5    0.07       0
  5839.4   0.035       0
Bank Sta=4966.8,4975.2
Exp/Cntr=0.3,0.1

Type RM Length L Ch R = 1,28193,591,591,591
BEGIN DESCRIPTION:
Mapping XS 121be620
END DESCRIPTION:
XS GIS Cut Line= 3
      1687242.62      7018553.18      1687798.21      7018608.74
      1688836.40      7018771.94
#Sta/Elev= 30
  4434.8 1580.81  4587.9 1576.33  4618.1 1573.71  4658.3 1572.40  4708.5 1564.88
  4819.1 1553.02  4846.7 1547.41  4869.3 1543.21  4949.7 1535.64  4995.8 1527.26
  4996.3 1526.76  5004.3 1527.26  5017.9 1531.41  5050.7 1531.81  5124.0 1535.63
  5278.3 1542.32  5408.5 1550.92  5471.1 1558.94  5516.3 1562.67  5546.7 1568.60
  5607.4 1571.07  5627.7 1574.48  5637.8 1573.02  5663.8 1575.44  5694.1 1575.60
  5769.4 1577.30  5793.9 1579.93  5830.1 1582.68  5960.4 1584.88  6044.1 1586.72
#Mann=8,-1,0
  4434.8    0.07       0  4846.7   0.035       0  4995.8   0.035       0
  5004.3   0.035       0  5124.0    0.07       0  5694.1   0.035       0
  5793.9    0.07       0  5960.4   0.035       0
Bank Sta=4995.8,5004.3
Exp/Cntr=0.3,0.1

Type RM Length L Ch R = 1,27602,556,556,556
BEGIN DESCRIPTION:
Mapping XS 27183063
END DESCRIPTION:
XS GIS Cut Line= 3
      1687076.03      7018903.90      1687601.16      7019120.90
      1688420.76      7019472.15
#Sta/Elev= 30
  4428.6 1577.83  4449.6 1577.07  4546.5 1574.34  4560.0 1573.20  4589.8 1568.41
  4626.8 1564.96  4629.2 1564.78  4666.4 1560.97  4719.7 1558.03  4801.1 1544.64
  4827.8 1540.72  4945.7 1534.13  5004.3 1528.15  5027.9 1527.89  5033.6 1529.00
  5051.4 1529.26  5070.7 1527.82  5071.2 1527.32  5079.3 1527.82  5109.8 1531.18
  5180.2 1529.78  5228.6 1532.49  5332.5 1535.74  5408.6 1540.35  5447.0 1544.45
  5545.0 1560.34  5642.9 1574.40  5666.1 1576.55  5732.1 1578.49  5888.5 1585.68
#Mann=9,-1,0
  4428.6   0.035       0  4449.6    0.07       0  4626.8   0.035       0
  4629.2    0.07       0  4801.1   0.035       0  5070.7   0.035       0
  5079.3   0.035       0  5228.6    0.07       0  5732.1   0.035       0
Bank Sta=5070.7,5079.3
Exp/Cntr=0.3,0.1

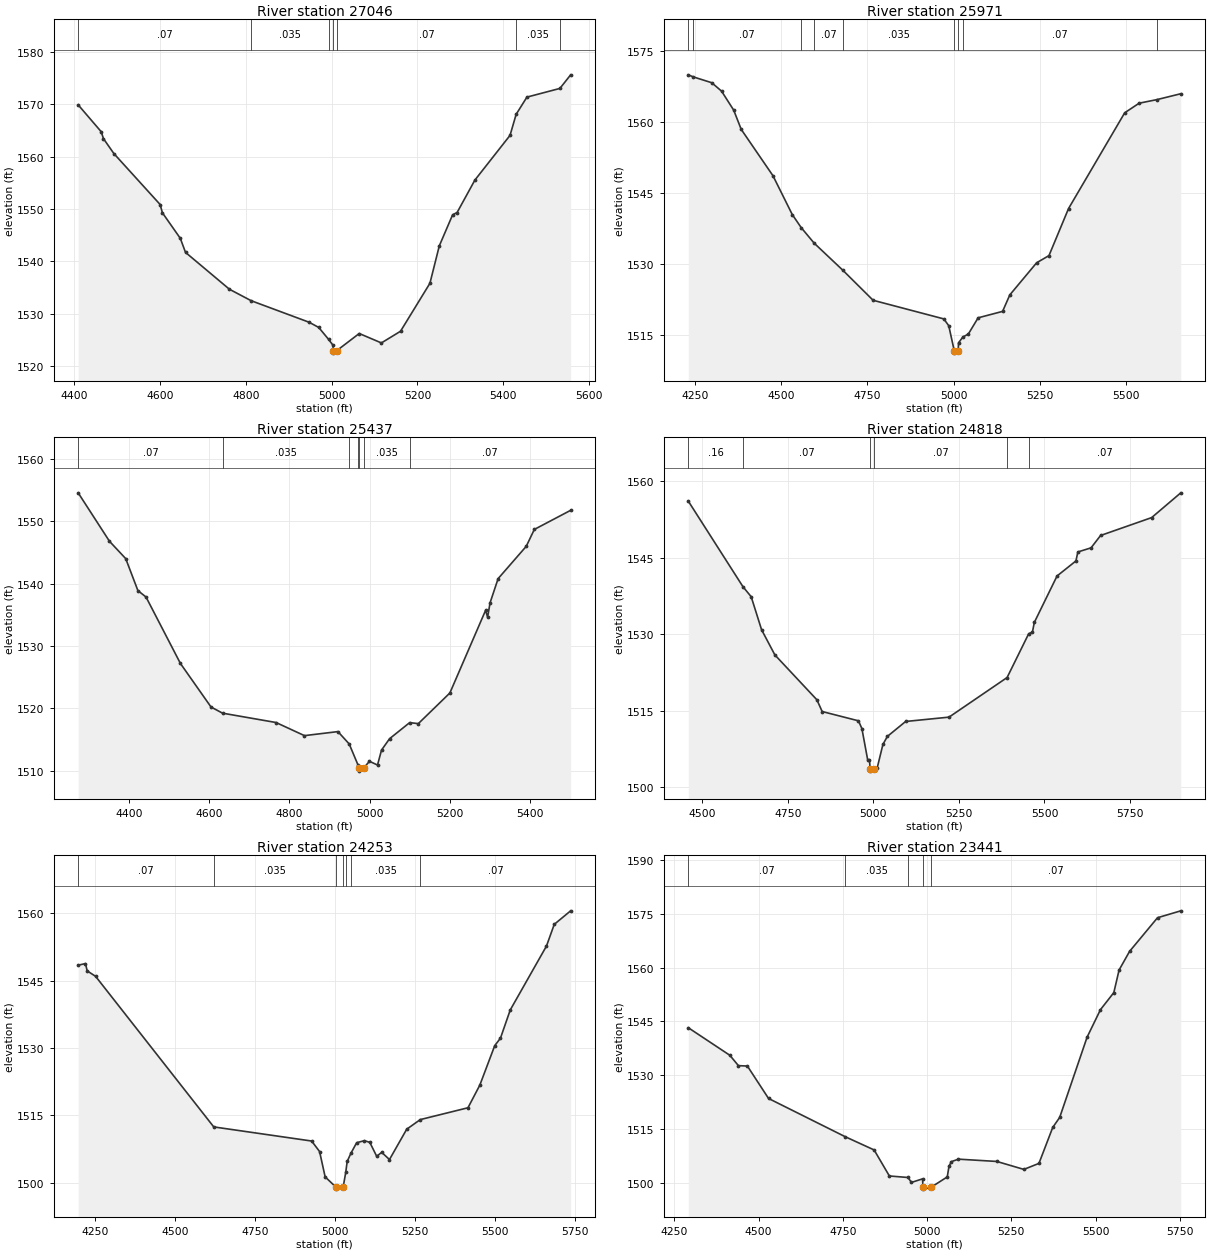
Type RM Length L Ch R = 1,27046,1075,1075,1075
BEGIN DESCRIPTION:
Mapping XS 1830c9b1
END DESCRIPTION:
XS GIS Cut Line= 3
      1686903.69      7019411.70      1687452.28      7019630.45
      1687990.27      7019779.69
#Sta/Elev= 30
  4408.6 1569.91  4462.3 1564.78  4467.7 1563.44  4491.9 1560.60  4599.8 1550.86
  4605.1 1549.28  4646.9 1544.39  4659.0 1541.71  4761.5 1534.66  4812.2 1532.47
  4947.5 1528.35  4969.8 1527.36  4992.6 1525.10  5003.2 1523.94  5003.7 1522.95
  5004.2 1522.45  5012.3 1522.95  5064.3 1526.20  5116.0 1524.40  5160.6 1526.63
  5229.2 1535.80  5251.1 1542.96  5282.2 1548.90  5292.6 1549.33  5334.1 1555.53
  5416.1 1564.08  5430.4 1568.11  5455.5 1571.39  5532.4 1573.05  5557.5 1575.65
#Mann=7,-1,0
  4408.6    0.07       0  4812.2   0.035       0  4992.6    0.07       0
  5003.7    0.07       0  5012.3    0.07       0  5430.4   0.035       0
  5532.4    0.07       0
Bank Sta=5003.7,5012.3
Exp/Cntr=0.3,0.1

Type RM Length L Ch R = 1,25971,534,534,534
BEGIN DESCRIPTION:
Mapping XS b71d9188
END DESCRIPTION:
XS GIS Cut Line= 3
      1686404.56      7019902.61      1686912.35      7020482.01
      1687355.04      7020968.11
#Sta/Elev= 30
  4230.7 1570.05  4245.2 1569.61  4298.7 1568.38  4327.1 1566.60  4362.3 1562.58
  4384.1 1558.51  4476.1 1548.71  4532.1 1540.50  4558.0 1537.73  4595.5 1534.45
  4678.5 1528.73  4766.5 1522.36  4971.5 1518.42  4985.8 1516.98  5001.8 1511.68
  5002.3 1511.18  5013.2 1511.68  5014.2 1513.37  5026.7 1514.58  5042.6 1515.22
  5071.0 1518.65  5141.9 1520.01  5162.9 1523.50  5240.6 1530.29  5276.4 1531.81
  5333.2 1541.77  5496.0 1562.02  5537.9 1564.05  5589.7 1564.81  5658.6 1566.05
#Mann=9,-1,0
  4230.7   0.035       0  4245.2    0.07       0  4558.0   0.035       0
  4595.5    0.07       0  4678.5   0.035       0  5001.8   0.035       0
  5013.2   0.035       0  5026.7    0.07       0  5589.7   0.035       0
Bank Sta=5001.8,5013.2
Exp/Cntr=0.3,0.1

Type RM Length L Ch R = 1,25437,619,619,619
BEGIN DESCRIPTION:
Mapping XS 78f0a92d
END DESCRIPTION:
XS GIS Cut Line= 3
      1686450.84      7020120.93      1686563.68      7020845.72
      1686591.89      7021338.39
#Sta/Elev= 30
  4273.8 1554.60  4351.8 1546.82  4392.3 1544.03  4422.6 1538.90  4442.9 1537.86
  4528.6 1527.19  4604.8 1520.20  4633.5 1519.21  4766.7 1517.71  4837.6 1515.60
  4921.0 1516.25  4949.1 1514.26  4971.4 1510.83  4972.5 1510.40  4973.0 1509.90
  4985.2 1510.40  4999.5 1511.48  5019.6 1510.88  5029.6 1513.28  5049.7 1515.11
  5099.7 1517.69  5121.3 1517.53  5199.9 1522.45  5288.9 1535.73  5293.9 1534.62
  5300.1 1536.95  5320.1 1540.82  5390.2 1546.01  5410.3 1548.72  5500.8 1551.79
#Mann=7,-1,0
  4273.8    0.07       0  4633.5   0.035       0  4949.1    0.07       0
  4971.4   0.035       0  4972.5   0.035       0  4985.2   0.035       0
  5099.7    0.07       0
Bank Sta=4972.5,4985.2
Exp/Cntr=0.3,0.1

Type RM Length L Ch R = 1,24818,565,565,565
BEGIN DESCRIPTION:
Mapping XS c0724b6a
END DESCRIPTION:
XS GIS Cut Line= 3
      1686087.98      7020256.20      1686007.26      7020795.23
      1686418.73      7021589.54
#Sta/Elev= 30
  4458.9 1556.13  4618.9 1539.32  4642.7 1537.38  4673.1 1530.90  4711.9 1525.97
  4834.8 1517.16  4850.2 1514.86  4956.2 1513.04  4966.3 1511.53  4983.4 1505.32
  4988.5 1505.40  4990.3 1503.67  4990.8 1503.17  5003.0 1503.67  5011.3 1503.87
  5027.8 1508.41  5040.8 1509.98  5094.2 1512.91  5221.0 1513.76  5390.8 1521.53
  5453.9 1530.12  5464.8 1530.44  5470.4 1532.35  5536.8 1541.45  5592.0 1544.40
  5597.6 1546.16  5636.2 1546.97  5664.0 1549.39  5813.3 1552.90  5898.5 1557.76
#Mann=6,-1,0
  4458.9    0.16       0  4618.9    0.07       0  4990.3    0.07       0
  5003.0    0.07       0  5390.8   0.035       0  5453.9    0.07       0
Bank Sta=4990.3,5003
Exp/Cntr=0.3,0.1

Type RM Length L Ch R = 1,24253,812,812,812
BEGIN DESCRIPTION:
Mapping XS 7265807b
END DESCRIPTION:
XS GIS Cut Line= 3
      1684871.80      7020904.59      1685637.46      7021159.82
      1685908.31      7021842.15
#Sta/Elev= 30
  4196.4 1548.43  4219.3 1548.78  4224.6 1547.16  4250.9 1545.95  4620.7 1512.45
  4927.1 1509.31  4951.9 1506.97  4969.3 1501.34  5002.2 1499.11  5002.7 1498.61
  5025.8 1499.11  5033.7 1502.31  5038.3 1504.77  5050.0 1506.60  5068.0 1508.94
  5092.3 1509.39  5109.1 1509.01  5130.6 1505.92  5146.3 1506.79  5170.6 1505.19
  5224.6 1511.94  5267.1 1514.08  5416.3 1516.71  5453.4 1521.75  5500.0 1530.52
  5518.0 1532.20  5548.6 1538.47  5662.0 1552.69  5686.3 1557.51  5737.6 1560.52
#Mann=7,-1,0
  4196.4    0.07       0  4620.7   0.035       0  5002.2   0.035       0
  5025.8   0.035       0  5033.7    0.07       0  5050.0   0.035       0
  5267.1    0.07       0
Bank Sta=5002.2,5025.8
Exp/Cntr=0.3,0.1

Type RM Length L Ch R = 1,23441,828,828,828
BEGIN DESCRIPTION:
Mapping XS b845e8ad
END DESCRIPTION:
XS GIS Cut Line= 3
      1684846.84      7020960.16      1685055.17      7021645.06
      1685252.61      7022364.68
#Sta/Elev= 30
  4291.1 1543.25  4414.3 1535.59  4439.9 1532.70  4466.5 1532.59  4529.3 1523.57
  4757.3 1512.91  4842.8 1509.24  4888.0 1502.00  4943.1 1501.58  4953.7 1500.21
  4986.6 1501.20  4987.8 1498.84  4988.3 1498.34  5011.5 1498.84  5059.9 1501.74
  5065.1 1504.73  5072.3 1505.99  5093.0 1506.68  5207.1 1506.04  5287.3 1503.83
  5332.1 1505.50  5373.0 1515.50  5393.7 1518.30  5475.1 1540.64  5514.8 1548.29
  5554.4 1553.03  5570.0 1559.31  5601.1 1564.49  5684.1 1573.86  5753.2 1575.78
#Mann=5,-1,0
  4291.1    0.07       0  4757.3   0.035       0  4943.1    0.07       0
  4987.8    0.07       0  5011.5    0.07       0
Bank Sta=4987.8,5011.5
Exp/Cntr=0.3,0.1

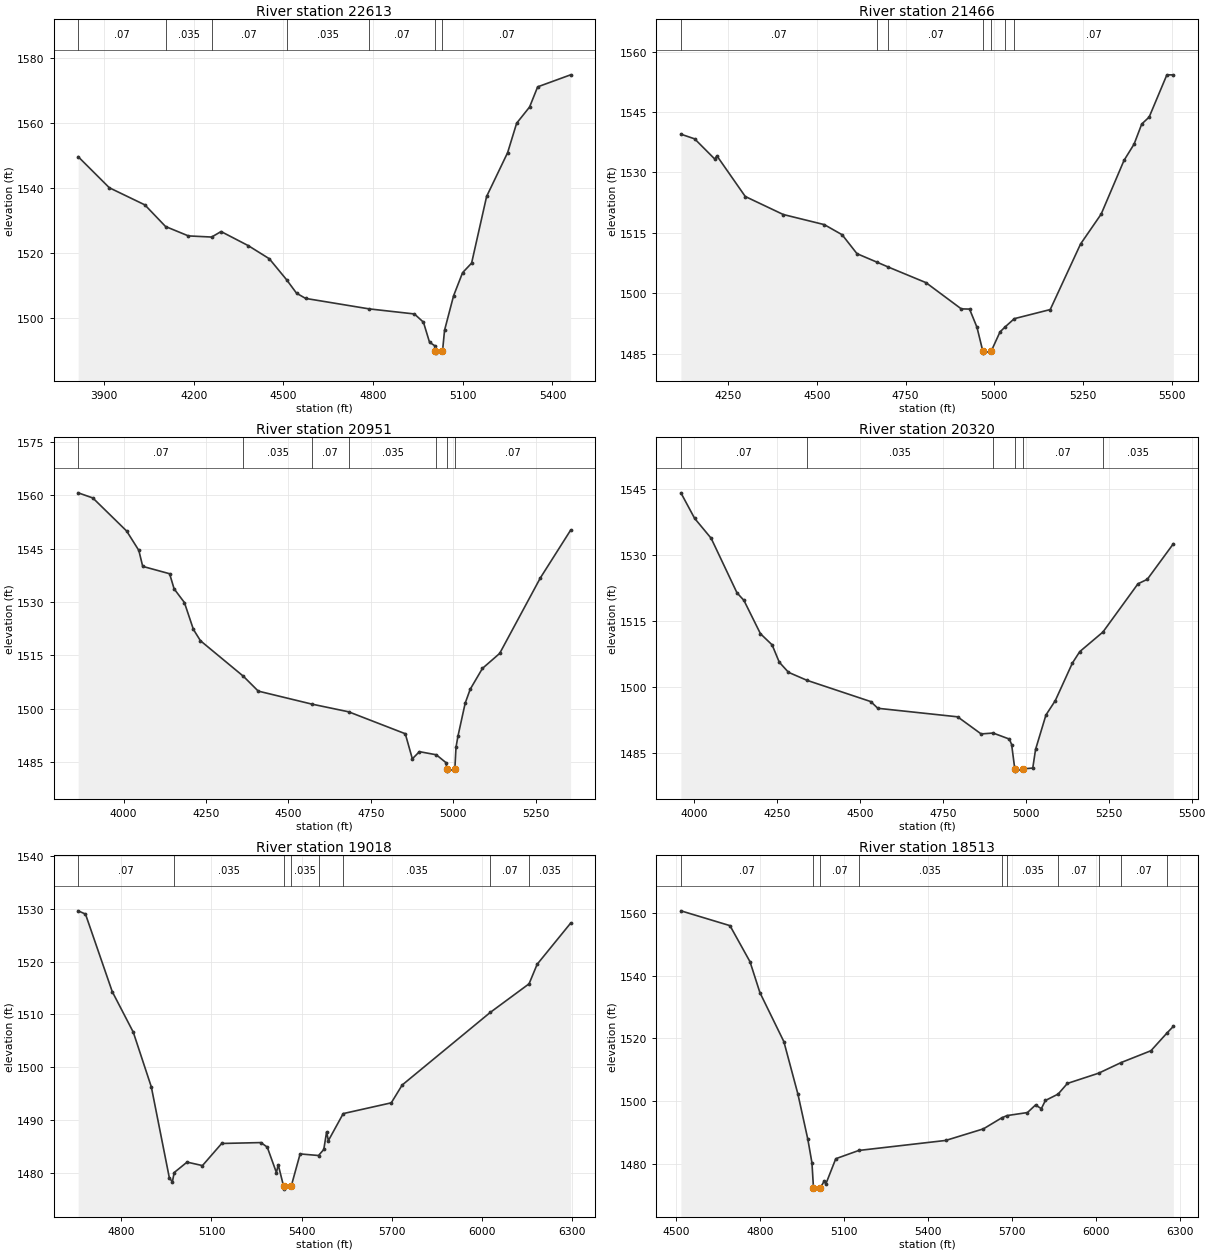
Type RM Length L Ch R = 1,22613,1147,1147,1147
BEGIN DESCRIPTION:
Mapping XS 7f7df5da
END DESCRIPTION:
XS GIS Cut Line= 3
      1684612.47      7020764.82      1684440.59      7021949.75
      1684396.32      7022397.64
#Sta/Elev= 30
  3813.2 1549.64  3917.5 1540.10  4036.5 1534.83  4105.6 1528.19  4182.0 1525.31
  4259.7 1524.96  4291.3 1526.65  4382.3 1522.32  4452.6 1518.30  4510.3 1511.87
  4543.9 1507.70  4574.3 1506.11  4786.4 1502.90  4938.0 1501.34  4968.3 1498.81
  4988.6 1492.67  5007.1 1491.51  5008.3 1489.81  5008.8 1489.31  5032.0 1489.81
  5038.9 1496.33  5069.1 1506.91  5099.2 1514.01  5129.4 1516.95  5179.6 1537.42
  5249.9 1550.88  5280.1 1559.92  5323.4 1564.90  5350.4 1571.09  5460.6 1574.78
#Mann=7,-1,0
  3813.2    0.07       0  4105.6   0.035       0  4259.7    0.07       0
  4510.3   0.035       0  4786.4    0.07       0  5008.3    0.07       0
  5032.0    0.07       0
Bank Sta=5008.3,5032
Exp/Cntr=0.3,0.1

Type RM Length L Ch R = 1,21466,515,515,515
BEGIN DESCRIPTION:
Mapping XS d27e8b74
END DESCRIPTION:
XS GIS Cut Line= 3
      1684226.07      7020516.48      1683713.05      7021234.67
      1683407.79      7021635.96
#Sta/Elev= 30
  4117.4 1539.48  4156.1 1538.32  4212.6 1533.32  4218.8 1534.10  4298.7 1524.00
  4405.6 1519.53  4521.1 1517.02  4571.5 1514.50  4613.3 1509.80  4670.4 1507.66
  4702.0 1506.46  4807.5 1502.61  4907.0 1496.09  4930.3 1496.04  4951.2 1491.52
  4967.6 1485.60  4968.1 1485.10  4991.4 1485.60  5016.0 1490.36  5031.2 1491.67
  5056.4 1493.66  5157.5 1495.92  5242.9 1512.20  5300.9 1519.62  5365.3 1532.97
  5393.7 1537.02  5415.2 1542.00  5436.1 1543.73  5486.0 1554.22  5504.2 1554.20
#Mann=7,-1,0
  4117.4    0.07       0  4670.4   0.035       0  4702.0    0.07       0
  4967.6    0.07       0  4991.4    0.07       0  5031.2   0.035       0
  5056.4    0.07       0
Bank Sta=4967.6,4991.4
Exp/Cntr=0.3,0.1

Type RM Length L Ch R = 1,20951,631,631,631
BEGIN DESCRIPTION:
Mapping XS 47ee3cdd
END DESCRIPTION:
XS GIS Cut Line= 3
      1683876.98      7020149.87      1683293.67      7021129.00
      1683114.21      7021433.31
#Sta/Elev= 30
  3862.4 1560.74  3906.8 1559.30  4009.3 1550.00  4046.3 1544.54  4058.1 1540.04
  4139.6 1537.97  4153.3 1533.72  4184.5 1529.87  4211.7 1522.32  4233.1 1519.12
  4362.9 1509.15  4408.4 1504.94  4570.5 1501.29  4682.6 1499.11  4854.2 1492.94
  4875.6 1485.88  4897.0 1487.90  4948.2 1487.02  4977.7 1484.80  4980.5 1482.92
  4981.0 1482.42  5004.4 1482.92  5008.0 1489.16  5013.9 1492.27  5035.8 1501.55
  5051.0 1505.46  5088.1 1511.33  5140.3 1515.54  5263.7 1536.80  5355.4 1550.22
#Mann=7,-1,0
  3862.4    0.07       0  4362.9   0.035       0  4570.5    0.07       0
  4682.6   0.035       0  4948.2    0.07       0  4980.5    0.07       0
  5004.4    0.07       0
Bank Sta=4980.5,5004.4
Exp/Cntr=0.3,0.1

Type RM Length L Ch R = 1,20320,1302,1302,1302
BEGIN DESCRIPTION:
Mapping XS cf774e0d
END DESCRIPTION:
XS GIS Cut Line= 3
      1683486.39      7020050.86      1682775.44      7020816.50
      1682585.35      7021212.30
#Sta/Elev= 30
  3960.9 1544.21  4002.2 1538.41  4052.1 1533.87  4129.8 1521.48  4150.8 1519.75
  4200.6 1512.17  4235.8 1509.63  4257.2 1505.71  4285.1 1503.39  4340.9 1501.57
  4532.9 1496.74  4554.4 1495.21  4794.8 1493.27  4865.6 1489.38  4901.8 1489.58
  4950.6 1488.21  4957.5 1486.97  4967.0 1481.42  4967.5 1480.92  4990.9 1481.42
  5021.2 1481.62  5029.6 1485.85  5060.9 1493.68  5089.1 1496.96  5140.5 1505.48
  5162.7 1508.09  5232.6 1512.55  5338.2 1523.52  5366.3 1524.54  5444.8 1532.62
#Mann=6,-1,0
  3960.9    0.07       0  4340.9   0.035       0  4901.8    0.07       0
  4967.0    0.07       0  4990.9    0.07       0  5232.6   0.035       0
Bank Sta=4967,4990.9
Exp/Cntr=0.3,0.1

Type RM Length L Ch R = 1,19018,505,505,505
BEGIN DESCRIPTION:
Mapping XS 582bf63b
END DESCRIPTION:
XS GIS Cut Line= 3
      1681748.62      7019744.90      1681772.06      7020093.84
      1682461.52      7021183.98
#Sta/Elev= 30
  4656.2 1529.61  4680.6 1528.99  4769.6 1514.31  4839.7 1506.62  4899.8 1496.25
  4960.0 1478.96  4970.0 1478.28  4975.9 1480.02  5018.8 1482.00  5070.0 1481.34
  5134.1 1485.53  5264.6 1485.70  5285.8 1484.84  5316.3 1480.01  5322.3 1481.50
  5340.4 1477.38  5340.9 1476.88  5365.3 1477.38  5395.2 1483.55  5456.5 1483.25
  5474.0 1484.39  5483.4 1487.72  5489.3 1486.07  5538.7 1491.19  5698.7 1493.23
  5735.1 1496.61  6028.5 1510.37  6157.5 1515.78  6184.4 1519.48  6295.8 1527.27
#Mann=8,-1,0
  4656.2    0.07       0  4975.9   0.035       0  5340.4   0.035       0
  5365.3   0.035       0  5456.5    0.07       0  5538.7   0.035       0
  6028.5    0.07       0  6157.5   0.035       0
Bank Sta=5340.4,5365.3
Exp/Cntr=0.3,0.1

Type RM Length L Ch R = 1,18513,710,710,710
BEGIN DESCRIPTION:
Mapping XS 5f2f9a70
END DESCRIPTION:
XS GIS Cut Line= 3
      1681024.68      7020093.86      1681415.28      7020385.51
      1682407.48      7021177.18
#Sta/Elev= 30
  4518.0 1560.62  4693.1 1555.90  4764.5 1544.42  4799.9 1534.58  4885.4 1518.96
  4935.4 1502.29  4970.9 1487.86  4985.5 1480.41  4990.9 1472.52  4991.4 1472.02
  5015.9 1472.52  5028.9 1474.52  5035.3 1473.71  5070.5 1481.70  5152.6 1484.33
  5462.8 1487.52  5597.3 1491.21  5661.9 1494.68  5681.3 1495.43  5754.3 1496.40
  5783.1 1498.80  5803.9 1497.64  5818.3 1500.24  5863.8 1502.28  5896.8 1505.67
  6008.3 1508.93  6088.9 1512.33  6194.9 1516.08  6252.2 1521.73  6274.8 1523.83
#Mann=10,-1,0
  4518.0    0.07       0  4990.9    0.07       0  5015.9    0.07       0
  5152.6   0.035       0  5661.9    0.07       0  5681.3   0.035       0
  5863.8    0.07       0  6008.3   0.035       0  6088.9    0.07       0
  6252.2   0.035       0
Bank Sta=4990.9,5015.9
Exp/Cntr=0.3,0.1

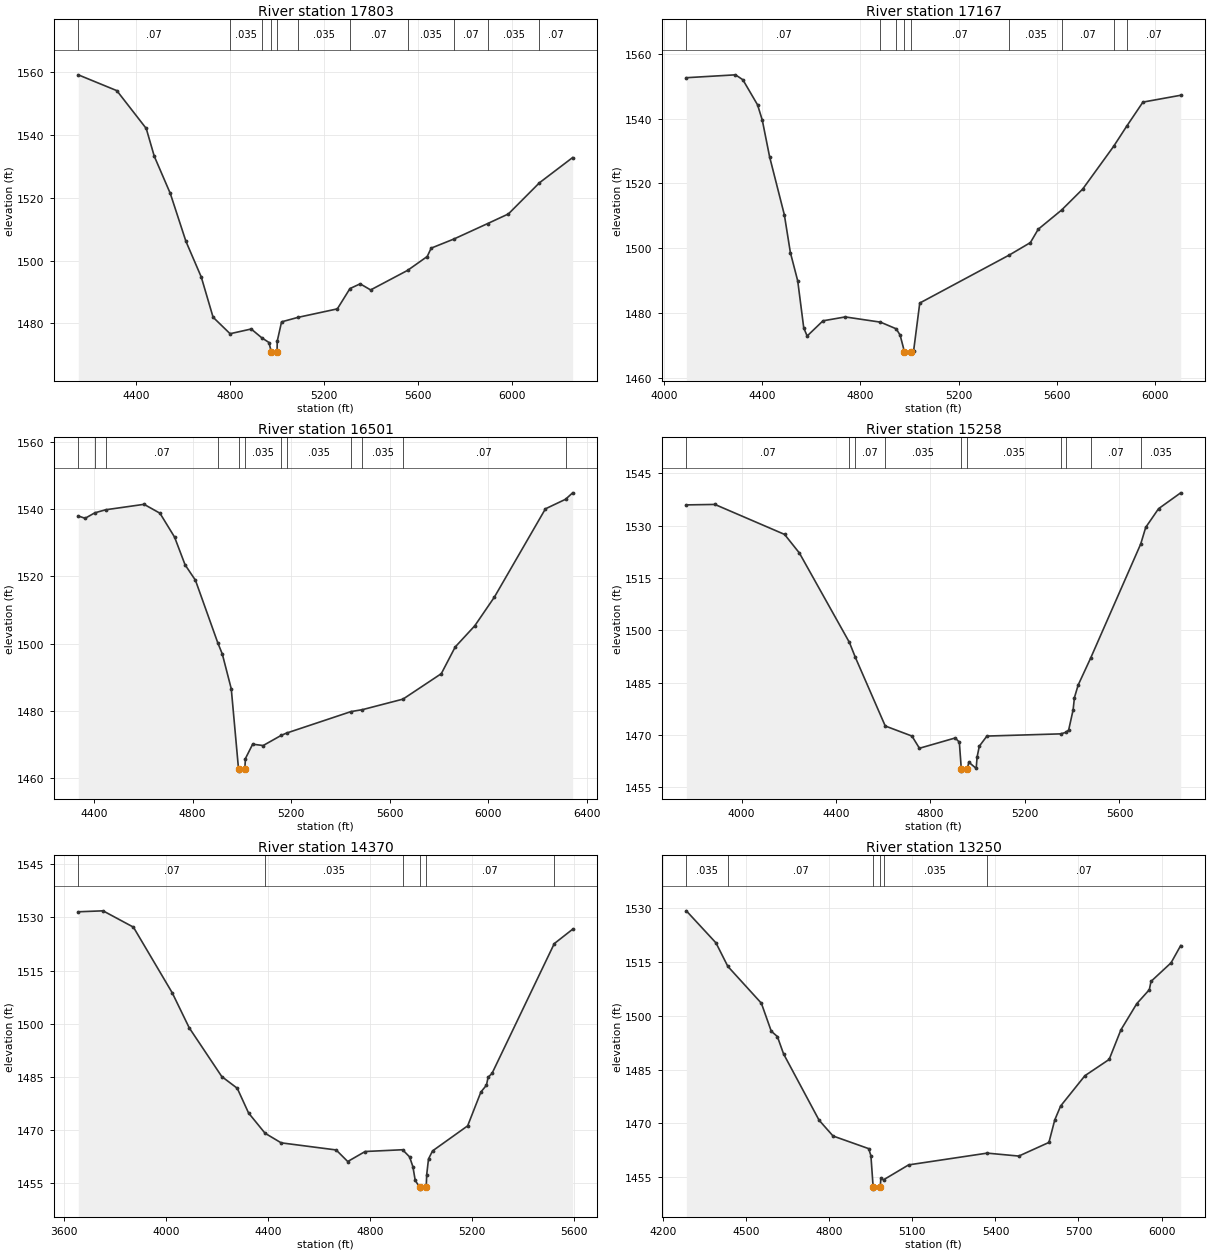
Type RM Length L Ch R = 1,17803,636,636,636
BEGIN DESCRIPTION:
Mapping XS 23b664f2
END DESCRIPTION:
XS GIS Cut Line= 3
      1680610.78      7020581.46      1681350.40      7020985.12
      1682556.15      7021362.73
#Sta/Elev= 30
  4152.5 1559.05  4316.8 1554.02  4442.1 1541.99  4476.3 1533.17  4544.6 1521.33
  4611.1 1506.13  4676.6 1494.75  4726.9 1481.98  4799.3 1476.74  4889.2 1478.24
  4933.7 1475.48  4965.1 1473.94  4974.4 1471.07  4974.9 1470.57  4999.5 1471.07
  5000.1 1474.35  5018.6 1480.51  5088.6 1481.94  5256.2 1484.64  5310.0 1491.10
  5353.5 1492.60  5398.1 1490.66  5555.7 1496.89  5639.1 1501.29  5656.0 1503.95
  5753.2 1506.86  5897.1 1511.78  5984.9 1514.82  6117.2 1524.73  6258.6 1532.75
#Mann=11,-1,0
  4152.5    0.07       0  4799.3   0.035       0  4933.7    0.07       0
  4974.4    0.07       0  4999.5    0.07       0  5088.6   0.035       0
  5310.0    0.07       0  5555.7   0.035       0  5753.2    0.07       0
  5897.1   0.035       0  6117.2    0.07       0
Bank Sta=4974.4,4999.5
Exp/Cntr=0.3,0.1

Type RM Length L Ch R = 1,17167,666,666,666
BEGIN DESCRIPTION:
Mapping XS a45fc446
END DESCRIPTION:
XS GIS Cut Line= 3
      1680456.51      7021249.44      1681302.87      7021577.57
      1682339.30      7021957.76
#Sta/Elev= 30
  4091.5 1552.58  4291.6 1553.47  4321.6 1551.95  4381.4 1544.21  4400.6 1539.50
  4430.5 1528.16  4490.4 1510.31  4514.9 1498.68  4544.8 1489.94  4569.4 1475.41
  4583.2 1472.95  4647.6 1477.63  4738.2 1478.83  4881.6 1477.22  4945.7 1475.16
  4961.5 1473.22  4978.8 1468.17  4979.3 1467.67  5004.0 1468.17  5016.3 1468.30
  5041.4 1483.11  5406.3 1497.94  5491.5 1501.74  5523.4 1505.86  5618.5 1511.78
  5704.5 1518.26  5830.2 1531.41  5883.0 1537.58  5949.5 1545.06  6103.2 1547.17
#Mann=9,-1,0
  4091.5    0.07       0  4881.6   0.035       0  4945.7    0.07       0
  4978.8    0.07       0  5004.0    0.07       0  5406.3   0.035       0
  5618.5    0.07       0  5830.2   0.035       0  5883.0    0.07       0
Bank Sta=4978.8,5004
Exp/Cntr=0.3,0.1

Type RM Length L Ch R = 1,16501,1243,1243,1243
BEGIN DESCRIPTION:
Mapping XS 1ac14800
END DESCRIPTION:
XS GIS Cut Line= 3
      1680285.98      7021588.24      1680848.49      7021949.36
      1681930.88      7022736.86
#Sta/Elev= 30
  4335.6 1537.95  4363.5 1537.27  4403.1 1538.90  4446.8 1539.80  4602.7 1541.42
  4667.2 1538.78  4726.6 1531.67  4769.2 1523.44  4811.4 1518.83  4901.8 1500.28
  4920.4 1496.90  4956.8 1486.55  4986.4 1462.58  4986.9 1462.08  5011.6 1462.58
  5014.3 1465.83  5043.6 1470.09  5086.3 1469.69  5160.0 1472.73  5181.8 1473.41
  5443.1 1479.79  5489.1 1480.36  5653.8 1483.49  5809.4 1491.06  5865.8 1498.99
  5945.4 1505.31  6025.0 1513.84  6232.1 1540.08  6313.8 1542.92  6342.6 1544.84
#Mann=12,-1,0
  4335.6    0.07       0  4403.1   0.035       0  4446.8    0.07       0
  4901.8   0.035       0  4986.4   0.035       0  5011.6   0.035       0
  5160.0    0.07       0  5181.8   0.035       0  5443.1    0.07       0
  5489.1   0.035       0  5653.8    0.07       0  6313.8   0.035       0
Bank Sta=4986.4,5011.6
Exp/Cntr=0.3,0.1

Type RM Length L Ch R = 1,15258,888,888,888
BEGIN DESCRIPTION:
Mapping XS a9e235da
END DESCRIPTION:
XS GIS Cut Line= 3
      1679924.89      7021803.55      1680320.71      7022970.19
      1680633.22      7023772.30
#Sta/Elev= 30
  3766.4 1535.99  3887.3 1536.12  4182.3 1527.52  4245.1 1522.18  4456.9 1496.52
  4482.0 1492.24  4608.5 1472.56  4721.5 1469.67  4753.2 1466.17  4904.5 1469.12
  4922.1 1467.93  4930.6 1460.11  4931.1 1459.61  4955.9 1460.11  4962.1 1462.19
  4993.5 1460.38  4997.3 1463.64  5006.7 1466.76  5038.9 1469.67  5351.2 1470.30
  5371.7 1470.71  5384.9 1471.39  5403.8 1477.19  5409.4 1480.72  5425.3 1484.33
  5477.8 1492.01  5690.0 1524.78  5711.1 1529.54  5765.5 1534.90  5859.2 1539.45
#Mann=10,-1,0
  3766.4    0.07       0  4456.9   0.035       0  4482.0    0.07       0
  4608.5   0.035       0  4930.6   0.035       0  4955.9   0.035       0
  5351.2    0.07       0  5371.7   0.035       0  5477.8    0.07       0
  5690.0   0.035       0
Bank Sta=4930.6,4955.9
Exp/Cntr=0.3,0.1

Type RM Length L Ch R = 1,14370,1120,1120,1120
BEGIN DESCRIPTION:
Mapping XS 797ffcb7
END DESCRIPTION:
XS GIS Cut Line= 3
      1679038.37      7022225.18      1679616.50      7023441.33
      1679905.57      7023956.96
#Sta/Elev= 30
  3657.0 1531.60  3754.1 1531.87  3873.2 1527.26  4025.5 1508.68  4091.9 1498.82
  4219.5 1485.04  4280.2 1481.73  4324.5 1474.75  4389.2 1469.02  4452.3 1466.31
  4667.8 1464.30  4713.2 1461.03  4781.4 1463.86  4928.2 1464.36  4955.6 1462.34
  4968.7 1459.55  4977.7 1455.71  4995.4 1453.73  4995.9 1453.23  5020.8 1453.73
  5022.7 1457.30  5029.8 1461.75  5045.6 1464.03  5183.2 1471.11  5235.2 1480.68
  5256.9 1482.60  5263.4 1484.85  5278.6 1485.91  5522.7 1522.60  5594.7 1526.67
#Mann=6,-1,0
  3657.0    0.07       0  4389.2   0.035       0  4928.2    0.07       0
  4995.4    0.07       0  5020.8    0.07       0  5522.7   0.035       0
Bank Sta=4995.4,5020.8
Exp/Cntr=0.3,0.1

Type RM Length L Ch R = 1,13250,1164,1164,1164
BEGIN DESCRIPTION:
Mapping XS afa033ad
END DESCRIPTION:
XS GIS Cut Line= 3
      1678095.63      7022949.11      1678679.00      7023357.99
      1679580.06      7023941.34
#Sta/Elev= 30
  4283.4 1529.21  4390.6 1520.27  4433.3 1513.74  4554.5 1503.47  4590.2 1495.68
  4612.3 1494.19  4634.7 1489.35  4762.8 1470.90  4813.4 1466.48  4942.1 1462.96
  4950.2 1460.97  4958.3 1452.18  4958.8 1451.68  4983.9 1452.18  4986.0 1454.69
  4995.7 1454.27  5086.3 1458.43  5370.2 1461.71  5484.4 1460.89  5593.2 1464.69
  5614.3 1470.96  5635.5 1474.84  5723.2 1483.28  5810.8 1487.81  5853.1 1496.03
  5910.5 1503.34  5955.9 1507.24  5961.9 1509.54  6034.4 1514.73  6069.2 1519.54
#Mann=6,-1,0
  4283.4   0.035       0  4433.3    0.07       0  4958.3   0.035       0
  4983.9    0.07       0  4995.7   0.035       0  5370.2    0.07       0
Bank Sta=4958.3,4983.9
Exp/Cntr=0.3,0.1