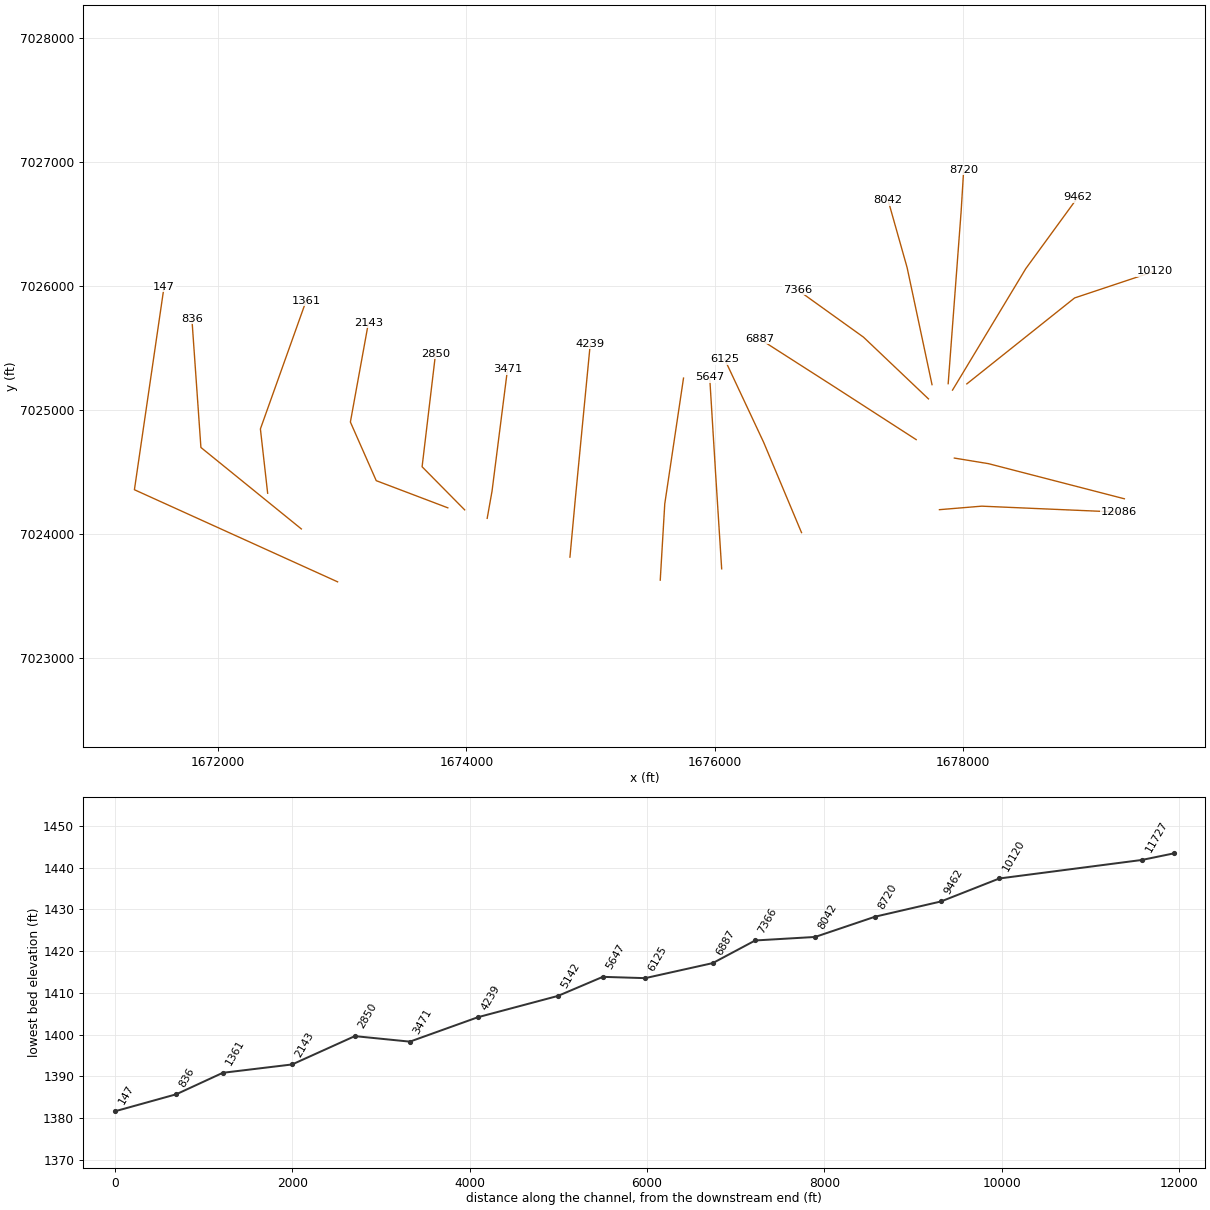
HEC-RAS study Antelope Creek.prj: Antelope Creek Base Level Engineering

--- Antelope Creek.g01 (geometry) --- (continued)

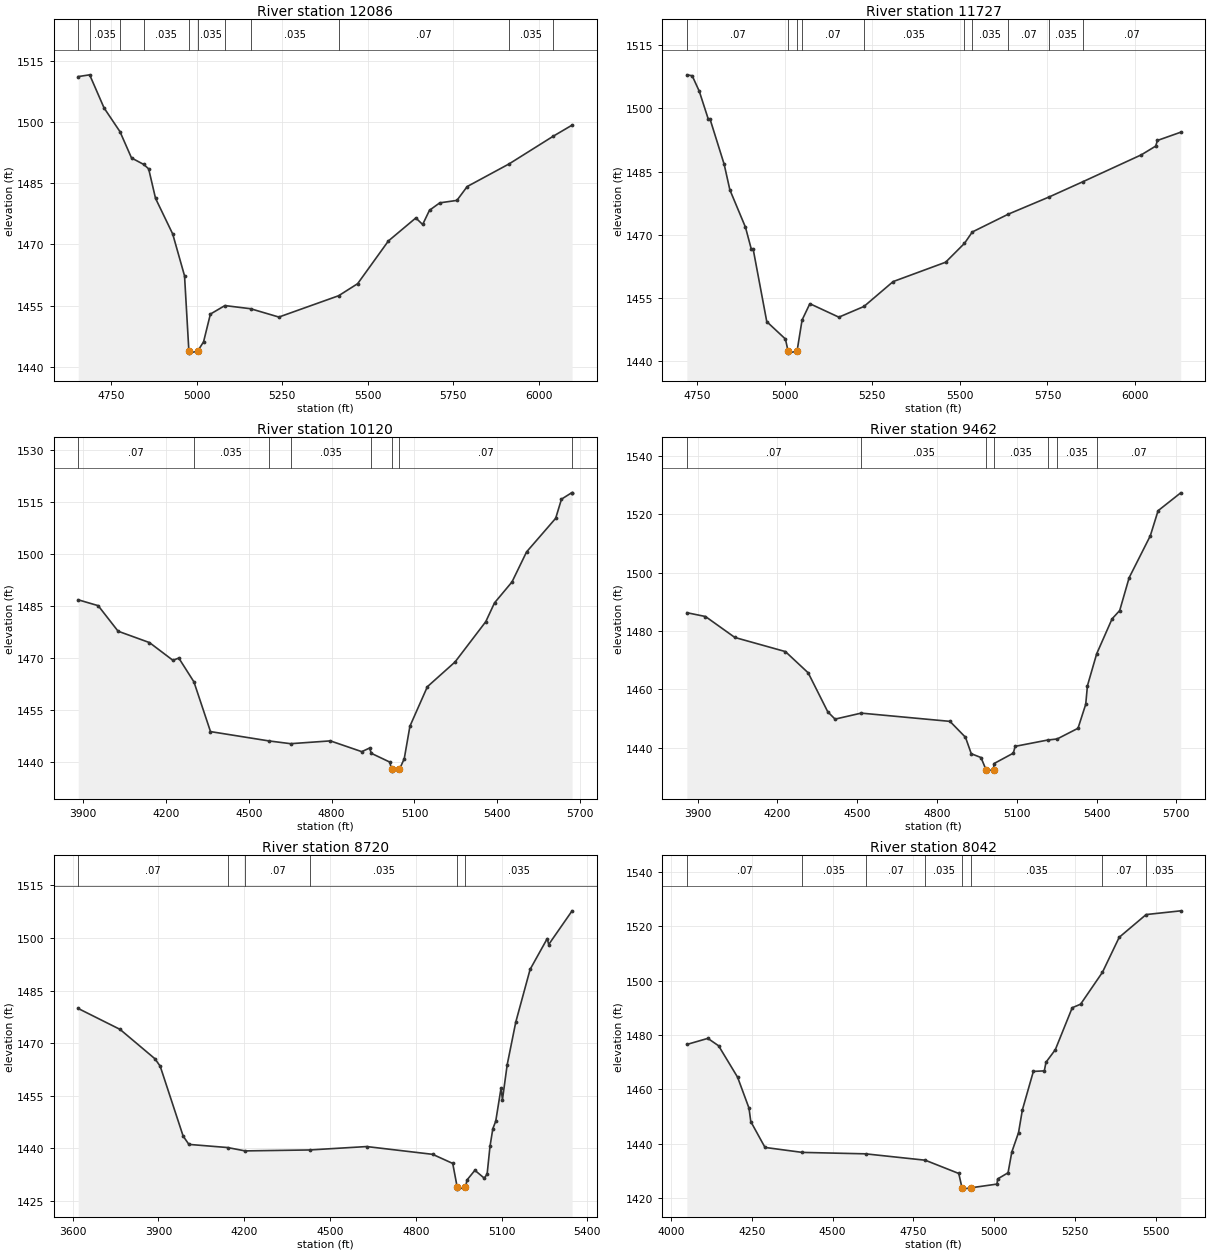
Type RM Length L Ch R = 1,12086,359,359,359
BEGIN DESCRIPTION:
Mapping XS ea3c624b
END DESCRIPTION:
XS GIS Cut Line= 3
      1677809.76      7024197.40      1678150.47      7024225.61
      1679251.46      7024177.93
#Sta/Elev= 30
  4653.9 1511.10  4687.3 1511.53  4729.4 1503.43  4776.0 1497.61  4809.7 1491.18
  4845.4 1489.59  4859.8 1488.51  4879.9 1481.29  4930.1 1472.57  4964.7 1462.32
  4977.4 1443.90  4977.9 1443.40  5003.1 1443.90  5020.3 1446.16  5040.3 1452.96
  5082.7 1455.04  5157.8 1454.27  5240.5 1452.23  5415.2 1457.45  5470.8 1460.40
  5560.8 1470.87  5640.9 1476.49  5660.9 1474.89  5680.9 1478.38  5711.0 1480.19
  5761.0 1480.79  5791.1 1484.18  5913.7 1489.73  6042.0 1496.47  6097.8 1499.22
#Mann=11,-1,0
  4653.9    0.07       0  4687.3   0.035       0  4776.0    0.07       0
  4845.4   0.035       0  4977.4   0.035       0  5003.1   0.035       0
  5082.7    0.07       0  5157.8   0.035       0  5415.2    0.07       0
  5913.7   0.035       0  6042.0    0.07       0
Bank Sta=4977.4,5003.1
Exp/Cntr=0.3,0.1

Type RM Length L Ch R = 1,11727,1607,1607,1607
BEGIN DESCRIPTION:
Mapping XS 6d624449
END DESCRIPTION:
XS GIS Cut Line= 3
      1677930.03      7024612.99      1678205.07      7024567.97
      1679299.31      7024285.12
#Sta/Elev= 30
  4721.3 1507.99  4736.5 1507.77  4756.7 1504.09  4782.6 1497.41  4787.7 1497.39
  4827.7 1486.73  4844.0 1480.64  4888.5 1471.76  4905.3 1466.50  4910.4 1466.58
  4949.3 1449.31  5002.5 1445.18  5010.0 1442.33  5010.5 1441.83  5035.7 1442.33
  5050.0 1449.70  5072.2 1453.58  5154.9 1450.38  5226.5 1452.92  5309.8 1458.84
  5459.5 1463.44  5513.3 1467.93  5535.6 1470.63  5638.7 1474.88  5755.2 1478.97
  5851.1 1482.58  6018.0 1488.98  6058.7 1491.04  6063.8 1492.39  6130.2 1494.35
#Mann=10,-1,0
  4721.3    0.07       0  5010.0    0.07       0  5035.7    0.07       0
  5050.0    0.07       0  5226.5   0.035       0  5513.3    0.07       0
  5535.6   0.035       0  5638.7    0.07       0  5755.2   0.035       0
  5851.1    0.07       0
Bank Sta=5010,5035.7
Exp/Cntr=0.3,0.1

Type RM Length L Ch R = 1,10120,658,658,658
BEGIN DESCRIPTION:
Mapping XS 1d6836e9
END DESCRIPTION:
XS GIS Cut Line= 3
      1678030.30      7025210.59      1678898.34      7025902.84
      1679541.48      7026117.22
#Sta/Elev= 30
  3882.5 1486.85  3954.7 1485.16  4026.8 1477.79  4140.5 1474.50  4225.3 1469.39
  4246.6 1470.04  4301.5 1463.15  4361.4 1448.81  4571.9 1446.13  4651.4 1445.32
  4795.4 1446.13  4909.1 1443.02  4937.3 1444.06  4943.8 1442.54  5010.3 1440.02
  5017.3 1437.90  5017.8 1437.40  5045.5 1437.90  5063.0 1441.00  5083.5 1450.37
  5146.7 1461.77  5246.9 1468.91  5358.2 1480.55  5389.8 1485.97  5453.1 1492.01
  5505.8 1500.67  5611.2 1510.37  5632.3 1515.91  5668.7 1517.73  5670.7 1517.64
#Mann=8,-1,0
  3882.5    0.07       0  4301.5   0.035       0  4571.9    0.07       0
  4651.4   0.035       0  4943.8    0.07       0  5017.3    0.07       0
  5045.5    0.07       0  5668.7   0.035       0
Bank Sta=5017.3,5045.5
Exp/Cntr=0.3,0.1

Type RM Length L Ch R = 1,9462,742,742,742
BEGIN DESCRIPTION:
Mapping XS 591c8eb7
END DESCRIPTION:
XS GIS Cut Line= 3
      1677915.28      7025160.69      1678505.54      7026139.39
      1678926.55      7026716.65
#Sta/Elev= 30
  3859.3 1486.25  3929.3 1484.94  4039.9 1477.75  4229.9 1472.91  4315.6 1465.62
  4389.4 1452.23  4416.7 1449.74  4514.9 1451.80  4848.8 1448.97  4907.2 1443.51
  4929.0 1437.87  4965.6 1436.56  4984.3 1432.40  4984.8 1431.90  5012.6 1432.40
  5014.4 1434.49  5087.1 1438.07  5094.0 1440.40  5216.0 1442.56  5251.9 1442.93
  5330.4 1446.60  5359.4 1454.83  5365.9 1461.21  5400.6 1472.15  5458.5 1484.14
  5487.2 1487.00  5522.7 1498.25  5602.3 1512.63  5631.6 1521.24  5716.7 1527.37
#Mann=7,-1,0
  3859.3    0.07       0  4514.9   0.035       0  4984.3   0.035       0
  5012.6   0.035       0  5216.0    0.07       0  5251.9   0.035       0
  5400.6    0.07       0
Bank Sta=4984.3,5012.6
Exp/Cntr=0.3,0.1

Type RM Length L Ch R = 1,8720,678,678,678
BEGIN DESCRIPTION:
Mapping XS 0314b4a9
END DESCRIPTION:
XS GIS Cut Line= 3
      1677880.14      7025212.18      1677984.31      7026597.61
      1678005.04      7026934.54
#Sta/Elev= 30
  3619.8 1479.86  3766.0 1473.89  3888.0 1465.50  3906.4 1463.37  3986.6 1443.42
  4006.7 1441.04  4142.0 1440.14  4203.3 1439.18  4429.1 1439.45  4628.5 1440.42
  4859.1 1438.20  4929.3 1435.60  4945.1 1428.76  4945.6 1428.26  4973.6 1428.76
  4979.4 1430.89  5006.8 1433.64  5039.6 1431.39  5049.6 1432.57  5059.6 1440.47
  5069.6 1445.54  5079.7 1447.67  5098.2 1457.10  5103.2 1453.85  5119.7 1463.78
  5149.8 1475.99  5199.9 1491.04  5259.8 1499.83  5264.8 1498.13  5346.7 1507.76
#Mann=6,-1,0
  3619.8    0.07       0  4142.0   0.035       0  4203.3    0.07       0
  4429.1   0.035       0  4945.1   0.035       0  4973.6   0.035       0
Bank Sta=4945.1,4973.6
Exp/Cntr=0.3,0.1

Type RM Length L Ch R = 1,8042,676,676,676
BEGIN DESCRIPTION:
Mapping XS 18aaedb4
END DESCRIPTION:
XS GIS Cut Line= 3
      1677749.94      7025204.38      1677549.41      7026147.09
      1677395.78      7026691.32
#Sta/Elev= 30
  4048.5 1476.53  4113.5 1478.76  4146.8 1476.04  4205.6 1464.50  4240.9 1453.15
  4246.5 1448.20  4290.5 1438.71  4405.8 1436.89  4601.8 1436.36  4786.7 1434.02
  4890.5 1429.15  4900.5 1423.90  4901.0 1423.40  4929.0 1423.90  5008.8 1425.25
  5010.9 1427.15  5043.1 1429.40  5054.8 1437.05  5075.6 1444.17  5087.5 1452.51
  5121.5 1466.63  5155.4 1466.83  5160.6 1470.00  5189.4 1474.59  5241.8 1490.01
  5267.8 1491.32  5335.4 1503.03  5387.3 1515.88  5470.7 1524.23  5577.8 1525.60
#Mann=8,-1,0
  4048.5    0.07       0  4405.8   0.035       0  4601.8    0.07       0
  4786.7   0.035       0  4900.5   0.035       0  4929.0   0.035       0
  5335.4    0.07       0  5470.7   0.035       0
Bank Sta=4900.5,4929
Exp/Cntr=0.3,0.1

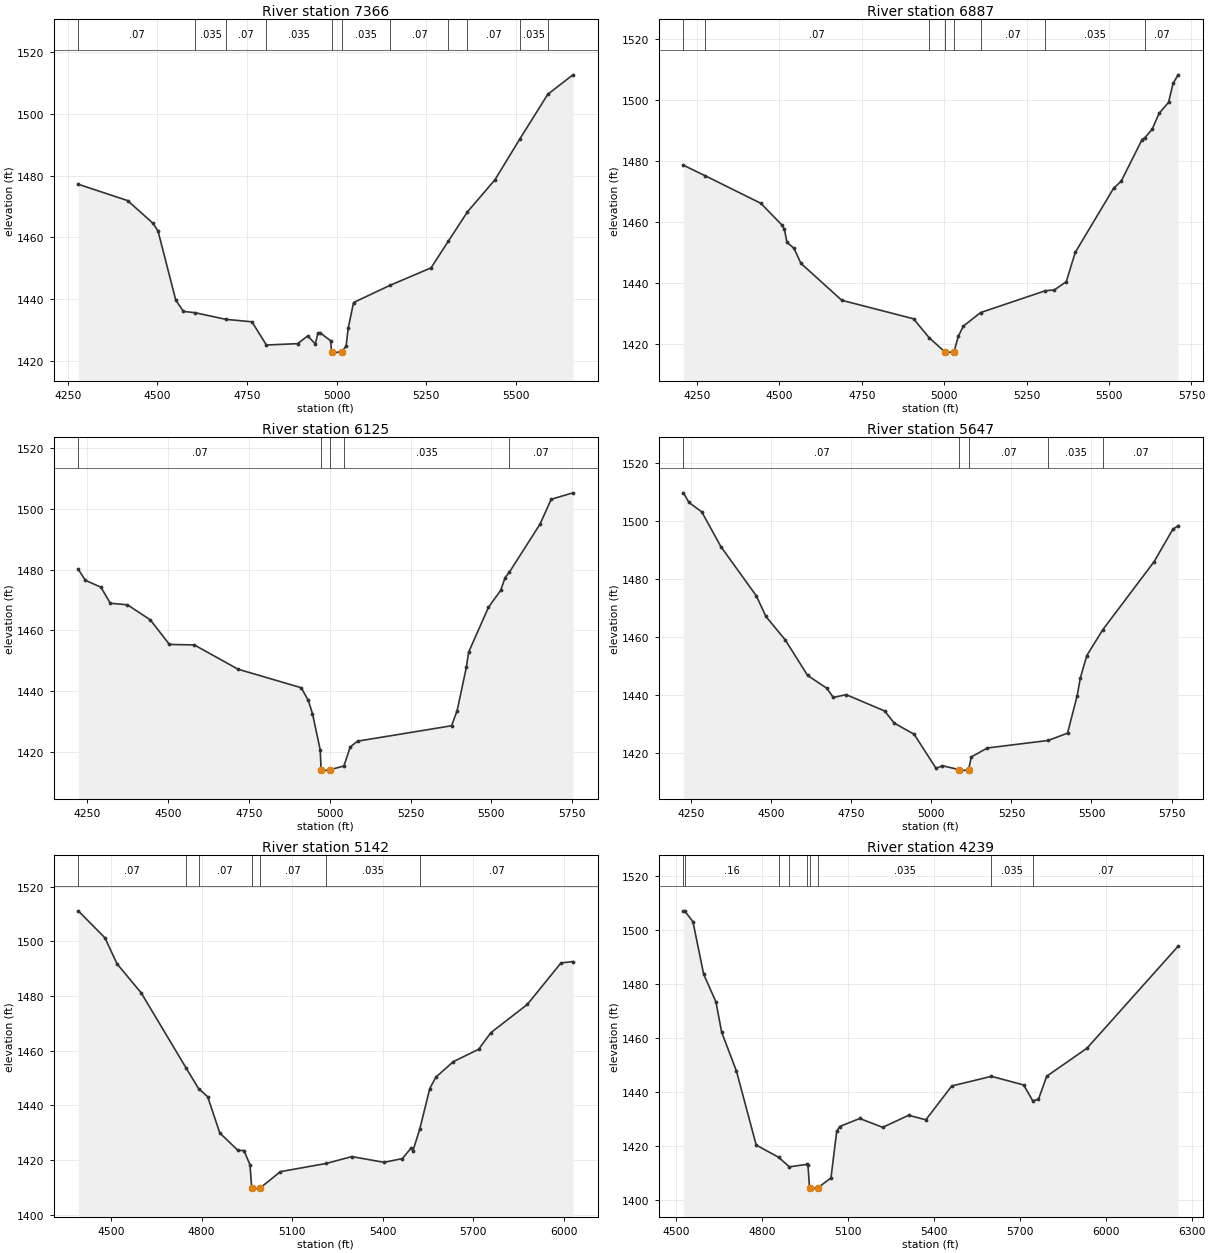
Type RM Length L Ch R = 1,7366,479,479,479
BEGIN DESCRIPTION:
Mapping XS 585f2af8
END DESCRIPTION:
XS GIS Cut Line= 3
      1677721.27      7025089.82      1677197.85      7025587.20
      1676663.97      7025970.03
#Sta/Elev= 30
  4279.6 1477.17  4417.1 1471.90  4487.9 1464.56  4502.0 1462.02  4551.4 1439.71
  4572.8 1436.06  4605.5 1435.63  4690.8 1433.49  4763.7 1432.69  4804.1 1425.19
  4891.1 1425.62  4919.4 1428.14  4940.5 1425.50  4947.8 1429.08  4954.7 1429.05
  4983.0 1426.58  4985.9 1423.06  4986.4 1422.56  5014.5 1423.06  5026.2 1424.82
  5032.3 1430.73  5047.1 1438.93  5149.8 1444.54  5263.2 1450.15  5311.6 1458.83
  5364.7 1468.27  5441.3 1478.64  5510.9 1491.88  5588.6 1506.28  5658.6 1512.57
#Mann=11,-1,0
  4279.6    0.07       0  4605.5   0.035       0  4690.8    0.07       0
  4804.1   0.035       0  4985.9   0.035       0  5014.5   0.035       0
  5149.8    0.07       0  5311.6   0.035       0  5364.7    0.07       0
  5510.9   0.035       0  5588.6    0.07       0
Bank Sta=4985.9,5014.5
Exp/Cntr=0.3,0.1

Type RM Length L Ch R = 1,6887,762,762,762
BEGIN DESCRIPTION:
Mapping XS 19056ba5
END DESCRIPTION:
XS GIS Cut Line= 3
      1677622.34      7024761.67      1676953.06      7025193.97
      1676360.58      7025573.36
#Sta/Elev= 30
  4209.0 1478.64  4274.1 1475.25  4443.9 1466.17  4507.9 1459.05  4515.4 1457.63
  4523.0 1453.38  4544.2 1451.49  4565.3 1446.53  4689.3 1434.43  4907.0 1428.38
  4954.0 1422.22  5001.0 1417.64  5001.5 1417.14  5029.7 1417.64  5043.0 1422.72
  5058.2 1426.00  5110.5 1430.42  5307.0 1437.57  5333.9 1437.82  5370.2 1440.51
  5397.3 1450.09  5514.1 1471.15  5536.8 1473.42  5600.2 1487.06  5608.9 1487.70
  5630.7 1490.42  5651.8 1495.64  5680.3 1499.19  5694.1 1505.40  5709.3 1508.23
#Mann=8,-1,0
  4209.0   0.035       0  4274.1    0.07       0  4954.0   0.035       0
  5001.0   0.035       0  5029.7   0.035       0  5110.5    0.07       0
  5307.0   0.035       0  5608.9    0.07       0
Bank Sta=5001,5029.7
Exp/Cntr=0.3,0.1

Type RM Length L Ch R = 1,6125,478,478,478
BEGIN DESCRIPTION:
Mapping XS b779352a
END DESCRIPTION:
XS GIS Cut Line= 3
      1676698.70      7024012.59      1676394.03      7024739.10
      1676079.48      7025409.79
#Sta/Elev= 30
  4223.2 1480.12  4245.5 1476.48  4293.1 1474.24  4322.3 1468.93  4375.2 1468.43
  4445.9 1463.44  4504.9 1455.34  4581.7 1455.19  4717.0 1447.17  4912.2 1441.06
  4933.9 1436.90  4947.0 1432.51  4970.8 1420.59  4973.7 1414.04  4974.2 1413.54
  5002.5 1414.04  5044.1 1415.24  5063.6 1421.51  5086.4 1423.43  5376.8 1428.51
  5394.1 1433.54  5422.4 1447.76  5429.5 1452.78  5490.9 1467.61  5528.9 1473.23
  5542.1 1477.37  5555.8 1479.25  5650.4 1495.08  5684.5 1503.23  5751.8 1505.37
#Mann=5,-1,0
  4223.2    0.07       0  4973.7    0.07       0  5002.5    0.07       0
  5044.1   0.035       0  5555.8    0.07       0
Bank Sta=4973.7,5002.5
Exp/Cntr=0.3,0.1

Type RM Length L Ch R = 1,5647,505,505,505
BEGIN DESCRIPTION:
Mapping XS 52a0bbda
END DESCRIPTION:
XS GIS Cut Line= 3
      1676055.49      7023720.90      1676006.01      7024499.52
      1675959.14      7025262.49
#Sta/Elev= 30
  4225.9 1509.57  4243.0 1506.28  4283.1 1503.03  4343.2 1491.01  4453.5 1474.14
  4483.5 1467.05  4543.6 1459.02  4613.8 1446.75  4673.9 1442.34  4693.9 1439.18
  4734.0 1440.16  4854.3 1434.54  4884.3 1430.36  4946.3 1426.53  5014.6 1414.84
  5034.6 1415.70  5087.5 1414.35  5088.0 1413.85  5116.3 1414.35  5124.8 1418.73
  5174.9 1421.81  5365.0 1424.40  5425.3 1426.91  5455.4 1439.77  5465.4 1445.92
  5485.5 1453.61  5535.3 1462.47  5695.9 1485.93  5753.7 1496.96  5770.5 1498.30
#Mann=5,-1,0
  4225.9    0.07       0  5087.5    0.07       0  5116.3    0.07       0
  5365.0   0.035       0  5535.3    0.07       0
Bank Sta=5087.5,5116.3
Exp/Cntr=0.3,0.1

Type RM Length L Ch R = 1,5142,903,903,903
BEGIN DESCRIPTION:
Mapping XS b58e2a74
END DESCRIPTION:
XS GIS Cut Line= 3
      1675560.70      7023629.69      1675597.16      7024244.31
      1675748.20      7025257.31
#Sta/Elev= 30
  4391.1 1511.18  4479.6 1501.28  4519.6 1491.77  4599.8 1481.13  4749.0 1453.57
  4790.1 1446.07  4820.2 1443.11  4860.2 1429.87  4920.3 1423.48  4940.4 1423.42
  4960.4 1418.21  4966.0 1409.79  4966.5 1409.29  4994.9 1409.79  5061.1 1415.68
  5213.0 1418.69  5298.0 1421.20  5404.8 1419.10  5465.5 1420.47  5495.8 1424.51
  5500.8 1423.40  5523.4 1431.33  5556.5 1446.13  5576.7 1450.28  5634.4 1455.96
  5718.3 1460.47  5758.7 1466.54  5880.0 1476.92  5991.3 1492.09  6031.0 1492.61
#Mann=7,-1,0
  4391.1    0.07       0  4749.0    0.16       0  4790.1    0.07       0
  4966.0    0.07       0  4994.9    0.07       0  5213.0   0.035       0
  5523.4    0.07       0
Bank Sta=4966,4994.9
Exp/Cntr=0.3,0.1

Type RM Length L Ch R = 1,4239,768,768,768
BEGIN DESCRIPTION:
Mapping XS 1fe7200b
END DESCRIPTION:
XS GIS Cut Line= 3
      1674833.27      7023814.99      1674877.54      7024294.14
      1674997.17      7025534.69
#Sta/Elev= 30
  4525.1 1506.97  4529.0 1506.97  4558.3 1502.98  4595.8 1483.56  4638.6 1473.35
  4658.7 1462.11  4710.4 1447.74  4779.2 1420.47  4858.0 1415.92  4895.1 1412.42
  4955.3 1413.32  4960.0 1413.03  4965.6 1404.69  4966.1 1404.19  4994.5 1404.69
  5040.3 1408.30  5060.4 1425.49  5070.4 1427.30  5141.0 1430.28  5221.1 1427.00
  5311.6 1431.47  5371.8 1429.80  5462.3 1442.29  5600.9 1445.85  5713.4 1442.66
  5744.9 1436.85  5764.9 1437.31  5793.8 1445.89  5934.4 1456.22  6252.6 1493.88
#Mann=9,-1,0
  4525.1    0.07       0  4529.0    0.16       0  4858.0   0.035       0
  4895.1    0.07       0  4955.3   0.035       0  4965.6    0.07       0
  4994.5   0.035       0  5600.9   0.035       0  5744.9    0.07       0
Bank Sta=4965.6,4994.5
Exp/Cntr=0.3,0.1

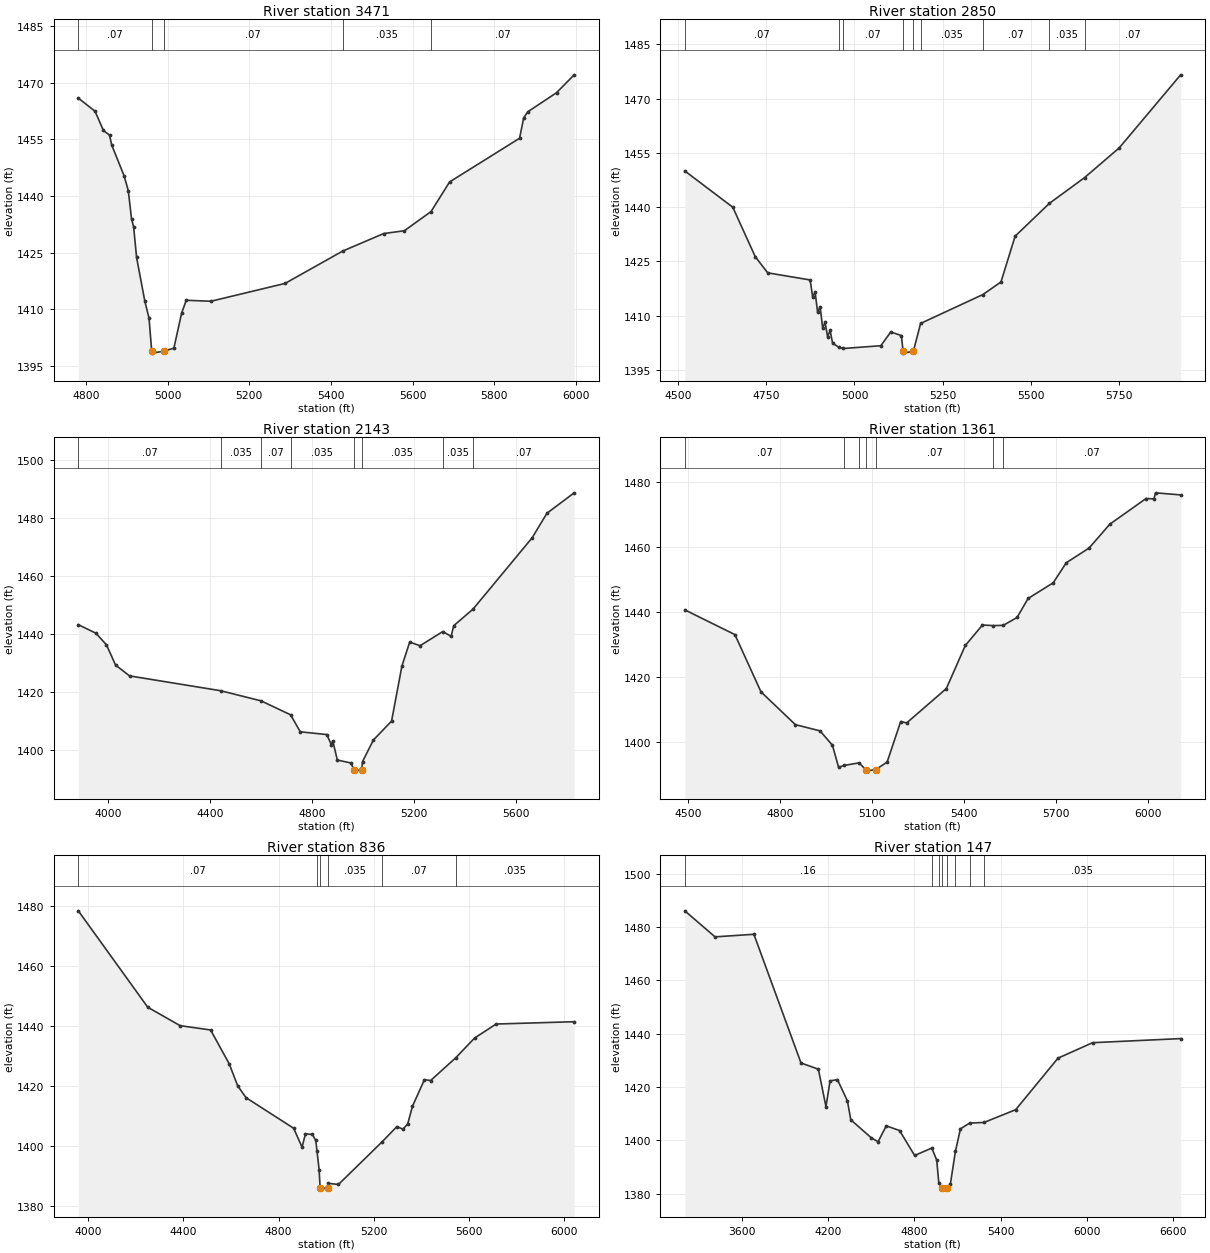
Type RM Length L Ch R = 1,3471,621,621,621
BEGIN DESCRIPTION:
Mapping XS 40362fcd
END DESCRIPTION:
XS GIS Cut Line= 3
      1674166.61      7024127.51      1674205.66      7024346.22
      1674330.67      7025330.64
#Sta/Elev= 30
  4781.1 1465.98  4822.2 1462.47  4842.5 1457.40  4857.5 1456.15  4862.9 1453.53
  4893.3 1445.33  4903.5 1441.42  4911.4 1433.96  4916.5 1431.86  4923.8 1423.72
  4944.1 1412.04  4954.3 1407.62  4960.8 1398.84  4961.3 1398.34  4989.9 1398.84
  5015.1 1399.65  5034.0 1408.90  5045.4 1412.36  5105.9 1412.10  5287.3 1416.82
  5428.5 1425.40  5529.2 1430.06  5579.6 1430.79  5645.1 1435.89  5690.5 1443.74
  5861.9 1455.33  5872.0 1460.76  5882.1 1462.35  5952.6 1467.42  5995.6 1472.15
#Mann=5,-1,0
  4781.1    0.07       0  4960.8    0.07       0  4989.9    0.07       0
  5428.5   0.035       0  5645.1    0.07       0
Bank Sta=4960.8,4989.9
Exp/Cntr=0.3,0.1

Type RM Length L Ch R = 1,2850,707,707,707
BEGIN DESCRIPTION:
Mapping XS 4c72a0e2
END DESCRIPTION:
XS GIS Cut Line= 3
      1673985.19      7024195.82      1673642.34      7024543.00
      1673750.76      7025453.73
#Sta/Elev= 30
  4519.2 1450.01  4655.2 1439.98  4718.9 1426.30  4754.2 1421.85  4874.4 1419.88
  4881.5 1415.21  4888.5 1416.51  4895.7 1410.89  4902.7 1412.51  4909.8 1406.68
  4916.8 1408.13  4923.9 1404.18  4931.0 1405.95  4938.1 1402.39  4955.2 1401.33
  4968.6 1400.94  5074.8 1401.71  5102.8 1405.50  5133.0 1404.51  5137.8 1400.16
  5138.3 1399.66  5166.9 1400.16  5187.5 1407.87  5364.2 1415.86  5415.2 1419.33
  5455.3 1431.98  5552.2 1441.03  5652.0 1448.16  5750.5 1456.40  5924.3 1476.57
#Mann=9,-1,0
  4519.2    0.07       0  4955.2   0.035       0  4968.6    0.07       0
  5137.8    0.07       0  5166.9    0.07       0  5187.5   0.035       0
  5364.2    0.07       0  5552.2   0.035       0  5652.0    0.07       0
Bank Sta=5137.8,5166.9
Exp/Cntr=0.3,0.1

Type RM Length L Ch R = 1,2143,782,782,782
BEGIN DESCRIPTION:
Mapping XS e1bd9c16
END DESCRIPTION:
XS GIS Cut Line= 4
      1673849.39      7024212.27      1673272.98      7024431.02
      1673064.65      7024903.25      1673210.04      7025702.88
#Sta/Elev= 30
  3883.6 1443.28  3952.5 1440.34  3994.1 1436.34  4029.6 1429.39  4084.6 1425.65
  4441.4 1420.56  4600.3 1417.07  4716.3 1412.27  4754.5 1406.41  4858.7 1405.46
  4876.5 1401.90  4882.0 1403.28  4899.8 1396.70  4951.9 1395.71  4966.1 1393.38
  4966.6 1392.88  4995.3 1393.38  4998.6 1396.16  5041.3 1403.58  5112.6 1410.10
  5153.1 1429.00  5183.7 1437.28  5224.4 1436.04  5313.9 1440.92  5346.3 1439.25
  5356.5 1442.93  5432.1 1448.62  5663.8 1473.13  5722.4 1481.64  5829.0 1488.65
#Mann=8,-1,0
  3883.6    0.07       0  4441.4   0.035       0  4600.3    0.07       0
  4716.3   0.035       0  4966.1    0.07       0  4995.3   0.035       0
  5313.9   0.035       0  5432.1    0.07       0
Bank Sta=4966.1,4995.3
Exp/Cntr=0.3,0.1

Type RM Length L Ch R = 1,1361,525,525,525
BEGIN DESCRIPTION:
Mapping XS 13fb2dca
END DESCRIPTION:
XS GIS Cut Line= 3
      1672398.23      7024329.87      1672339.82      7024847.69
      1672707.89      7025878.97
#Sta/Elev= 30
  4488.8 1440.62  4652.2 1432.98  4737.1 1415.33  4849.2 1405.22  4929.7 1403.29
  4970.0 1398.86  4990.1 1392.06  5007.8 1392.63  5057.1 1393.44  5078.0 1391.38
  5078.6 1390.88  5111.6 1391.38  5148.3 1393.68  5192.5 1406.18  5212.0 1405.75
  5341.2 1416.33  5403.1 1429.63  5459.1 1435.95  5493.9 1435.76  5527.0 1435.84
  5571.7 1438.27  5607.8 1444.13  5689.6 1448.96  5732.2 1455.14  5806.6 1459.69
  5874.4 1467.06  5992.3 1474.96  6017.8 1474.83  6023.1 1476.71  6104.9 1476.07
#Mann=7,-1,0
  4488.8    0.07       0  5007.8   0.035       0  5057.1    0.07       0
  5078.0    0.07       0  5111.6    0.07       0  5493.9   0.035       0
  5527.0    0.07       0
Bank Sta=5078,5111.6
Exp/Cntr=0.3,0.1

Type RM Length L Ch R = 1,836,689,689,689
BEGIN DESCRIPTION:
Mapping XS 8f966562
END DESCRIPTION:
XS GIS Cut Line= 3
      1672669.69      7024042.13      1671860.66      7024698.39
      1671787.86      7025734.80
#Sta/Elev= 30
  3960.0 1478.30  4251.4 1446.23  4387.2 1440.11  4515.1 1438.67  4593.4 1427.38
  4628.6 1420.11  4663.8 1416.15  4863.6 1405.99  4898.8 1399.70  4913.1 1404.12
  4941.9 1403.93  4956.3 1401.96  4961.7 1398.32  4970.4 1392.25  4974.6 1386.24
  4975.2 1385.74  5008.3 1386.24  5008.7 1387.69  5051.5 1387.28  5235.9 1401.56
  5296.8 1406.55  5322.1 1405.68  5342.2 1407.42  5362.2 1413.31  5412.4 1422.15
  5438.3 1421.85  5543.7 1429.42  5622.9 1435.99  5713.1 1440.65  6040.7 1441.42
#Mann=6,-1,0
  3960.0    0.07       0  4961.7   0.035       0  4974.6   0.035       0
  5008.3   0.035       0  5235.9    0.07       0  5543.7   0.035       0
Bank Sta=4974.6,5008.3
Exp/Cntr=0.3,0.1

Type RM Length L Ch R = 1,147,0,0,0
BEGIN DESCRIPTION:
Antelope Creek 1.0
END DESCRIPTION:
XS GIS Cut Line= 3
      1672961.52      7023616.09      1671324.94      7024358.02
      1671563.84      7025993.77
#Sta/Elev= 30
  3203.1 1486.03  3413.5 1476.27  3683.9 1477.23  4011.8 1428.97  4132.5 1426.66
  4185.3 1412.62  4213.9 1422.26  4265.5 1422.73  4334.8 1414.72  4357.9 1407.69
  4501.9 1400.86  4548.1 1399.45  4605.2 1405.41  4697.6 1403.65  4802.3 1394.30
  4921.7 1397.08  4956.0 1392.56  4970.3 1384.15  4993.2 1382.18  4993.9 1381.68
  5026.9 1382.18  5050.5 1383.42  5086.1 1395.85  5121.2 1404.30  5185.4 1406.46
  5284.7 1406.67  5505.3 1411.46  5799.8 1430.79  6040.9 1436.59  6653.1 1438.12
#Mann=8,-1,0
  3203.1    0.16       0  4921.7    0.07       0  4970.3    0.16       0
  4993.2    0.07       0  5026.9    0.16       0  5086.1    0.07       0
  5185.4    0.16       0  5284.7   0.035       0
Bank Sta=4993.2,5026.9
Exp/Cntr=0.3,0.1

Chan Stop Cuts=-1