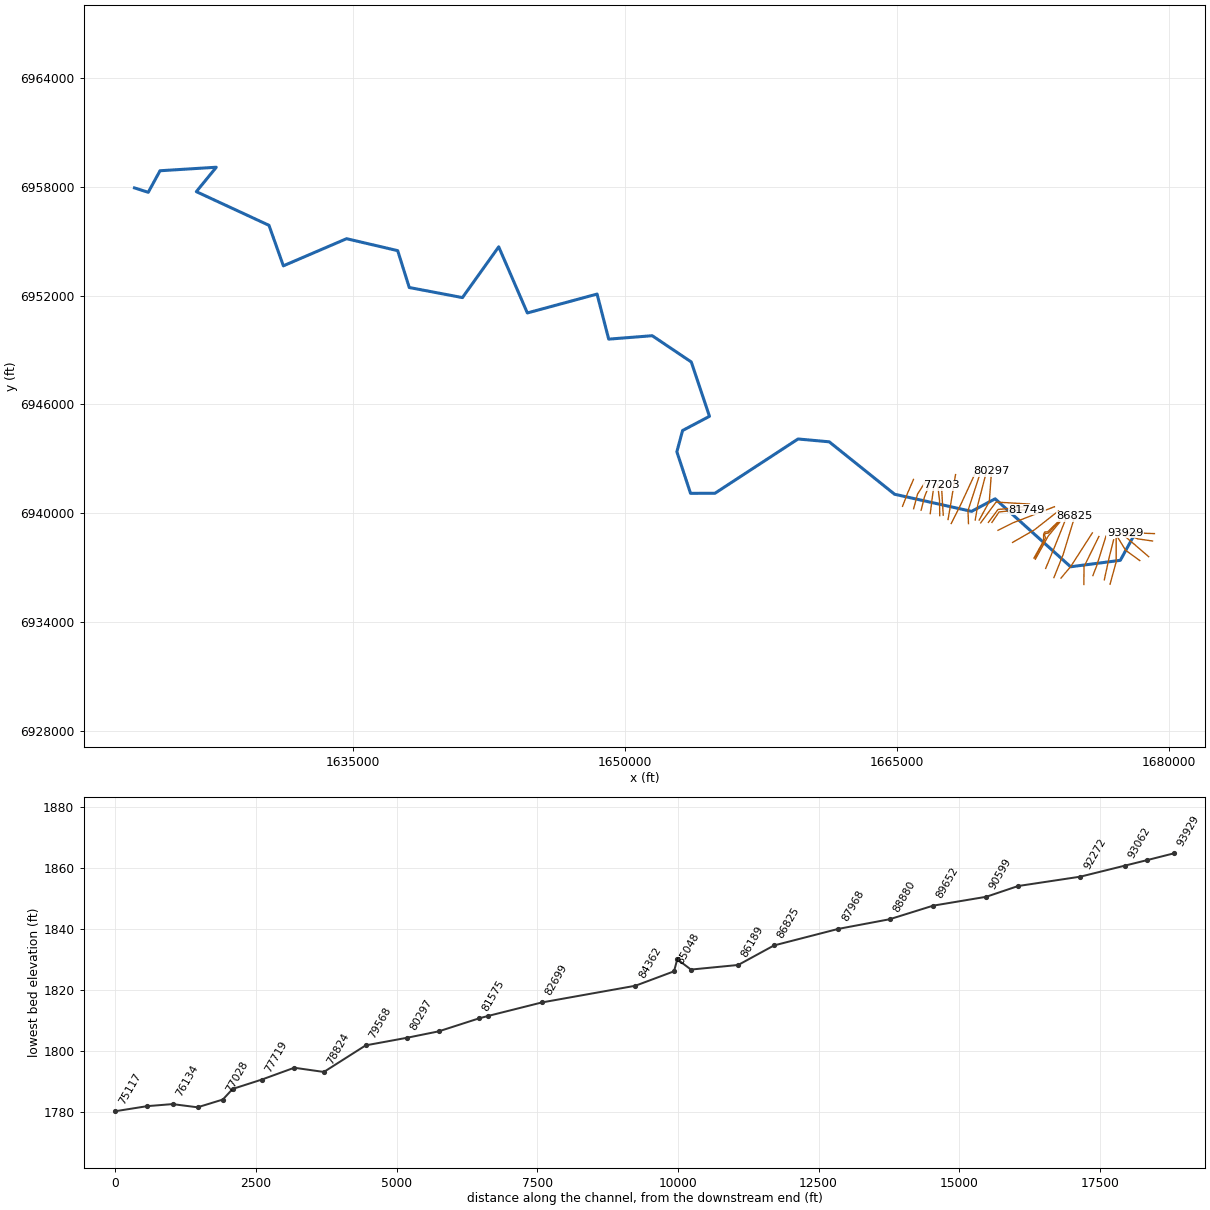
--- Chimney Creek.prj (project) ---

Proj Title=Chimney Creek Base Level Engineering
Current Plan=p01
Default Exp/Contr=0.3,0.1
English Units
Geom File=g01
Flow File=f01
Plan File=p01
BEGIN DESCRIPTION:
Chimney Creek
END DESCRIPTION:

--- Chimney Creek.p01 (plan) ---

Plan Title=Multiple Run
Short Identifier=Multiple
Geom File=g01
Flow File=f01
Subcritical Flow
K Sum by GR= 0
Std Step Tol= 0.01
Critical Tol= 0.01
Num of Std Step Trials= 20
Max Error Tol= 0.3
Flow Tol Ratio= 0.001
Split Flow NTrial= 30
Split Flow Tol= 0.02
Split Flow Ratio= 0.02
Log Output Level= 0
Friction Slope Method= 1
Unsteady Friction Slope Method= 2
Unsteady Bridges Friction Slope Method= 1
Parabolic Critical Depth
Global Vel Dist=  1 , 1 , 1
Global Log Level= 0
CheckData=True
Encroach Param= -1, 0, 0, 0
BEGIN DESCRIPTION:
Multiple Run
END DESCRIPTION:

--- Chimney Creek.f01 (steady flow) ---

Flow Title=Multiple
Number of Profiles=7
Profile Names=10-year,25-year,50-year,1pct_min,100-year,1pct_plu,500-year
River Rch & RM= Chimney Creek,Reach-1,93929
     227     310     378     229     458     913     680
River Rch & RM= Chimney Creek,Reach-1,92272
     262     360     440     268     534    1065     797
River Rch & RM= Chimney Creek,Reach-1,89652
     395     556     690     426     851    1697    1309
River Rch & RM= Chimney Creek,Reach-1,85349
     447     632     787     487     972    1940    1502
River Rch & RM= Chimney Creek,Reach-1,80297
     633     910    1147     717    1431    2856    2261
River Rch & RM= Chimney Creek,Reach-1,77203
     714    1031    1302     816    1629    3250    2584
River Rch & RM= Chimney Creek,Reach-1,68866
     802    1164    1475     928    1851    3694    2955
River Rch & RM= Chimney Creek,Reach-1,67160
     815    1180    1494     938    1873    3736    2980
River Rch & RM= Chimney Creek,Reach-1,61182
    1697    2528    3265    2087    4164    8309    6867
River Rch & RM= Chimney Creek,Reach-1,54975
    1712    2550    3292    2104    4197    8375    6915
River Rch & RM= Chimney Creek,Reach-1,51714
    1807    2691    3472    2218    4426    8830    7285
River Rch & RM= Chimney Creek,Reach-1,41666
    1847    2751    3551    2268    4525    9029    7450
River Rch & RM= Chimney Creek,Reach-1,39518
    1885    2809    3626    2317    4622    9223    7611
River Rch & RM= Chimney Creek,Reach-1,37366
    1930    2877    3715    2374    4737    9452    7806
River Rch & RM= Chimney Creek,Reach-1,33372
    1940    2887    3725    2378    4746    9469    7803
River Rch & RM= Chimney Creek,Reach-1,29048
    1969    2931    3781    2413    4815    9607    7914
River Rch & RM= Chimney Creek,Reach-1,23090
    1983    2948    3801    2424    4837    9651    7939
River Rch & RM= Chimney Creek,Reach-1,19983
    2033    3028    3907    2495    4978    9931    8185
River Rch & RM= Chimney Creek,Reach-1,15518
    2276    3400    4398    2814    5614   11202    9269
River Rch & RM= Chimney Creek,Reach-1,8196
    2337    3494    4521    2894    5774   11521    9541
River Rch & RM= Chimney Creek,Reach-1,4991
    2553    3826    4960    3180    6345   12660   10518
Boundary for River Rch & Prof#=Chimney Creek,Reach-1,1
Up Type=0
Dn Type=3
Dn Slope=0.00012
Boundary for River Rch & Prof#=Chimney Creek,Reach-1,2
Up Type=0
Dn Type=3
Dn Slope=0.00012
Boundary for River Rch & Prof#=Chimney Creek,Reach-1,3
Up Type=0
Dn Type=3
Dn Slope=0.00012
Boundary for River Rch & Prof#=Chimney Creek,Reach-1,4
Up Type=0
Dn Type=3
Dn Slope=0.00012
Boundary for River Rch & Prof#=Chimney Creek,Reach-1,5
Up Type=0
Dn Type=3
Dn Slope=0.00012
Boundary for River Rch & Prof#=Chimney Creek,Reach-1,6
Up Type=0
Dn Type=3
Dn Slope=0.00012
Boundary for River Rch & Prof#=Chimney Creek,Reach-1,7
Up Type=0
Dn Type=3
Dn Slope=0.00012

--- Chimney Creek.g01 (geometry) ---

Geom Title=Existing Conditions

River Reach=Chimney Creek,Reach-1
Reach XY= 30
      1678155.00      6938938.00      1677307.36      6937393.76
      1674566.53      6937039.36      1670405.00      6940788.00
      1669105.11      6940095.31      1664860.85      6941040.06
      1661257.45      6943932.53      1659536.73      6944087.79
      1654957.43      6941093.52      1653610.93      6941090.24
      1652857.26      6943382.06      1653171.43      6944554.76
      1654655.96      6945338.33      1653651.39      6948336.50
      1651499.06      6949785.74      1649098.93      6949596.13
      1648457.47      6952082.55      1644613.49      6951040.65
      1643034.97      6954687.96      1641034.91      6951887.89
      1638102.70      6952443.83      1637464.83      6954477.53
      1634645.35      6955136.64      1631160.85      6953640.06
      1630368.24      6955874.39      1626361.95      6957731.85
      1627461.73      6959078.89      1624360.94      6958885.74
      1623711.21      6957695.80      1622955.00      6957938.00

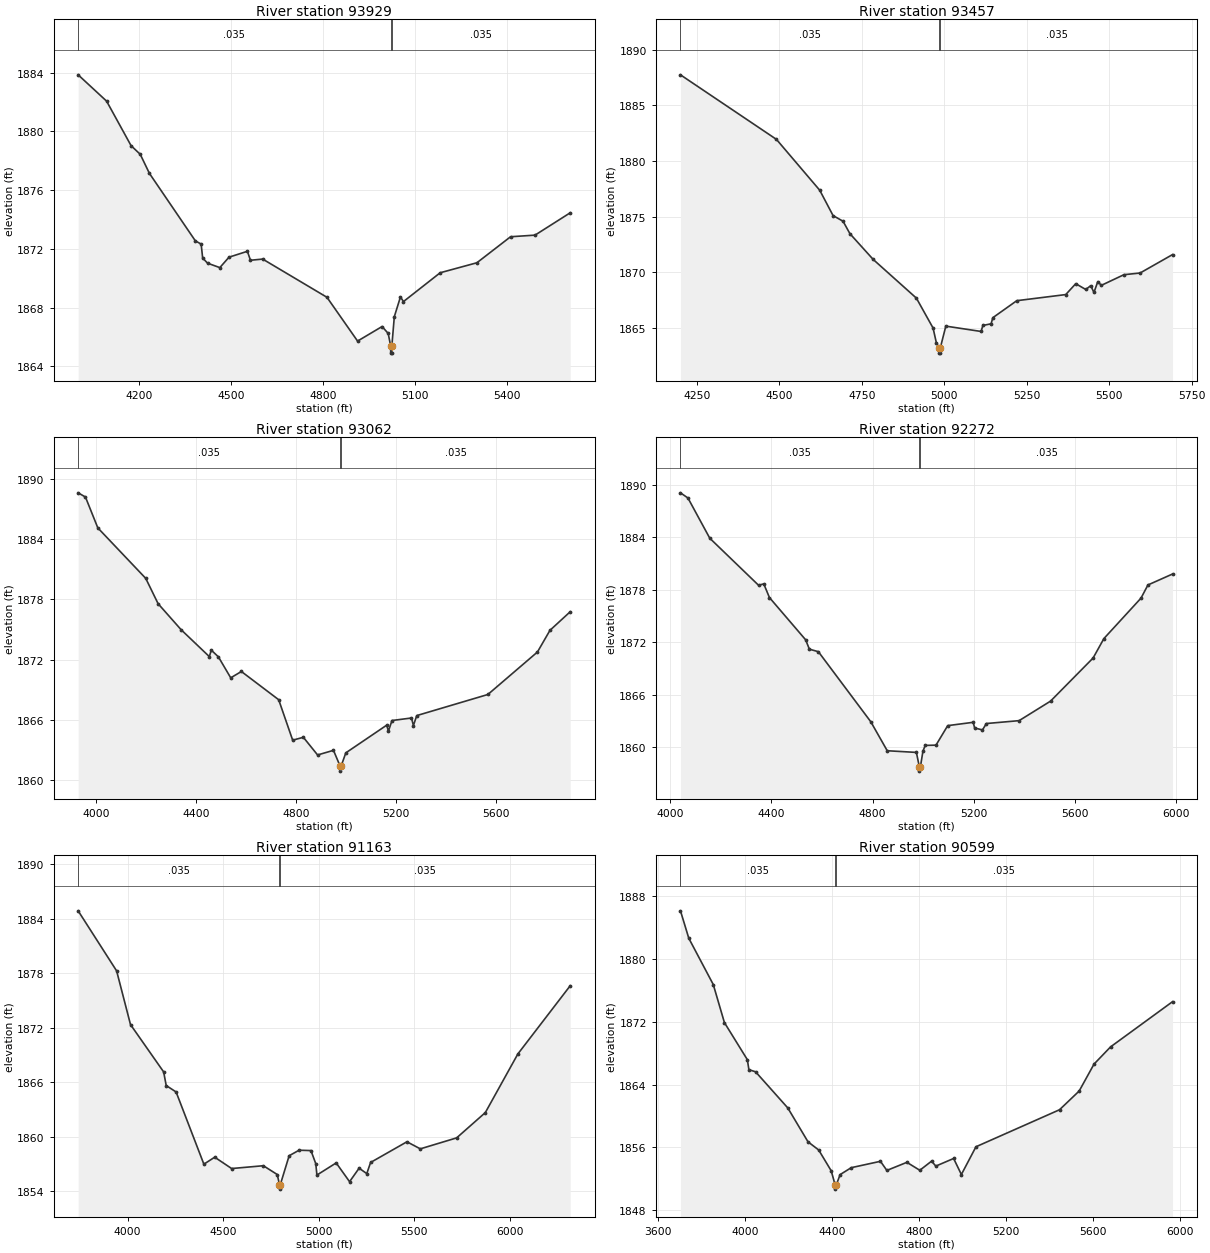
Type RM Length L Ch R = 1,93929,472,472,472
BEGIN DESCRIPTION:
Chimney Creek 159.0
END DESCRIPTION:
XS GIS Cut Line= 3
      1679187.90      6938868.23      1678188.16      6938904.63
      1677580.02      6938913.00
#Sta/Elev= 30
  3999.6 1883.85  4092.6 1882.06  4172.6 1879.03  4202.6 1878.44  4232.7 1877.14
  4382.8 1872.55  4401.7 1872.33  4406.7 1871.38  4422.8 1871.03  4462.8 1870.73
  4492.8 1871.44  4552.9 1871.84  4562.9 1871.23  4602.9 1871.31  4813.0 1868.71
  4913.1 1865.73  4993.2 1866.72  5013.2 1866.25  5021.2 1865.41  5021.4 1864.91
  5024.9 1864.91  5025.2 1865.41  5033.2 1867.39  5053.2 1868.73  5063.2 1868.42
  5183.2 1870.38  5303.2 1871.06  5413.2 1872.83  5493.2 1872.94  5608.2 1874.46
#Mann=3,-1,0
  3999.6   0.035       0  5021.2   0.035       0  5025.2   0.035       0
Bank Sta=5021.2,5025.2
Exp/Cntr=0.3,0.1

Type RM Length L Ch R = 1,93457,395,395,395
BEGIN DESCRIPTION:
Mapping XS 3f7e9d1f
END DESCRIPTION:
XS GIS Cut Line= 3
      1679082.92      6938460.74      1678283.41      6938575.33
      1677642.82      6938814.90
#Sta/Elev= 30
  4200.4 1887.76  4491.3 1881.95  4622.6 1877.37  4663.0 1875.09  4693.3 1874.58
  4714.1 1873.46  4784.7 1871.14  4915.6 1867.66  4966.1 1864.97  4976.2 1863.63
  4984.3 1863.21  4984.5 1862.71  4988.0 1862.71  4988.3 1863.21  5004.8 1865.14
  5111.7 1864.66  5117.1 1865.20  5142.0 1865.35  5147.3 1865.90  5219.9 1867.43
  5368.3 1867.98  5398.6 1868.96  5428.9 1868.44  5444.1 1868.78  5453.8 1868.17
  5465.5 1869.15  5476.1 1868.81  5544.7 1869.77  5593.6 1869.92  5692.0 1871.58
#Mann=3,-1,0
  4200.4   0.035       0  4984.3   0.035       0  4988.3   0.035       0
Bank Sta=4984.3,4988.3
Exp/Cntr=0.3,0.1

Type RM Length L Ch R = 1,93062,790,790,790
BEGIN DESCRIPTION:
Mapping XS 7b9e67d8
END DESCRIPTION:
XS GIS Cut Line= 3
      1678871.93      6937593.58      1678054.25      6938301.89
      1677374.54      6938872.22
#Sta/Elev= 30
  3928.9 1888.61  3958.2 1888.19  4007.6 1885.12  4199.5 1880.09  4248.9 1877.57
  4341.0 1874.98  4454.0 1872.30  4461.6 1872.95  4490.1 1872.28  4539.5 1870.19
  4582.2 1870.82  4731.4 1868.01  4787.4 1863.98  4830.1 1864.27  4887.1 1862.51
  4950.7 1862.97  4977.2 1861.40  4977.5 1860.90  4981.2 1861.40  5000.1 1862.72
  5163.9 1865.48  5170.5 1864.87  5184.8 1865.94  5262.8 1866.19  5270.6 1865.44
  5283.9 1866.43  5568.5 1868.53  5766.9 1872.76  5817.0 1874.92  5898.0 1876.77
#Mann=3,-1,0
  3928.9   0.035       0  4977.2   0.035       0  4981.2   0.035       0
Bank Sta=4977.2,4981.2
Exp/Cntr=0.3,0.1

Type RM Length L Ch R = 1,92272,1109,1109,1109
BEGIN DESCRIPTION:
Mapping XS 6b317ea1
END DESCRIPTION:
XS GIS Cut Line= 3
      1678378.87      6937381.35      1677601.99      6937947.73
      1677088.39      6938784.22
#Sta/Elev= 30
  4041.6 1889.10  4071.1 1888.51  4157.4 1883.91  4349.8 1878.54  4370.6 1878.69
  4392.9 1877.13  4535.9 1872.30  4550.6 1871.23  4586.2 1870.94  4793.2 1862.93
  4858.1 1859.62  4973.2 1859.43  4984.8 1857.79  4985.1 1857.29  4989.1 1857.79
  4999.0 1859.56  5008.0 1860.23  5050.6 1860.26  5096.9 1862.49  5197.4 1862.87
  5203.3 1862.22  5234.2 1862.00  5249.6 1862.73  5378.8 1863.06  5502.9 1865.29
  5671.0 1870.22  5713.6 1872.44  5860.0 1877.06  5887.6 1878.57  5984.6 1879.82
#Mann=3,-1,0
  4041.6   0.035       0  4984.8   0.035       0  4989.1   0.035       0
Bank Sta=4984.8,4989.1
Exp/Cntr=0.3,0.1

Type RM Length L Ch R = 1,91163,564,564,564
BEGIN DESCRIPTION:
Mapping XS 1425aa58
END DESCRIPTION:
XS GIS Cut Line= 3
      1676740.87      6936074.00      1677077.68      6937299.72
      1677081.16      6938601.76
#Sta/Elev= 30
  3741.7 1884.89  3942.9 1878.27  4015.5 1872.35  4188.9 1867.13  4202.2 1865.63
  4254.0 1864.92  4399.2 1856.96  4455.9 1857.73  4544.4 1856.48  4710.3 1856.79
  4782.9 1855.82  4794.6 1854.71  4794.9 1854.21  4799.0 1854.71  4845.1 1857.89
  4897.0 1858.50  4959.2 1858.46  4984.5 1857.01  4990.3 1855.76  5091.1 1857.10
  5161.1 1855.03  5211.1 1856.52  5251.1 1855.92  5271.1 1857.15  5461.1 1859.43
  5531.1 1858.65  5721.1 1859.86  5871.1 1862.65  6041.1 1869.11  6314.9 1876.63
#Mann=3,-1,0
  3741.7   0.035       0  4794.6   0.035       0  4799.0   0.035       0
Bank Sta=4794.6,4799
Exp/Cntr=0.3,0.1

Type RM Length L Ch R = 1,90599,947,947,947
BEGIN DESCRIPTION:
Mapping XS ca755b5f
END DESCRIPTION:
XS GIS Cut Line= 3
      1676424.91      6936320.56      1676702.68      6937594.86
      1676938.48      6938524.19
#Sta/Elev= 30
  3701.9 1886.10  3740.2 1882.61  3852.8 1876.72  3904.0 1871.88  4009.5 1867.16
  4016.6 1865.89  4047.3 1865.62  4195.5 1861.02  4288.5 1856.71  4337.6 1855.67
  4395.2 1853.02  4413.5 1851.19  4413.8 1850.69  4417.9 1851.19  4436.2 1852.54
  4487.4 1853.42  4621.7 1854.23  4651.1 1853.07  4743.2 1854.10  4802.6 1853.09
  4856.8 1854.25  4876.3 1853.62  4958.2 1854.59  4993.8 1852.55  5060.9 1856.08
  5445.2 1860.79  5535.5 1863.17  5603.9 1866.60  5680.0 1868.79  5964.9 1874.54
#Mann=3,-1,0
  3701.9   0.035       0  4413.5   0.035       0  4417.9   0.035       0
Bank Sta=4413.5,4417.9
Exp/Cntr=0.3,0.1

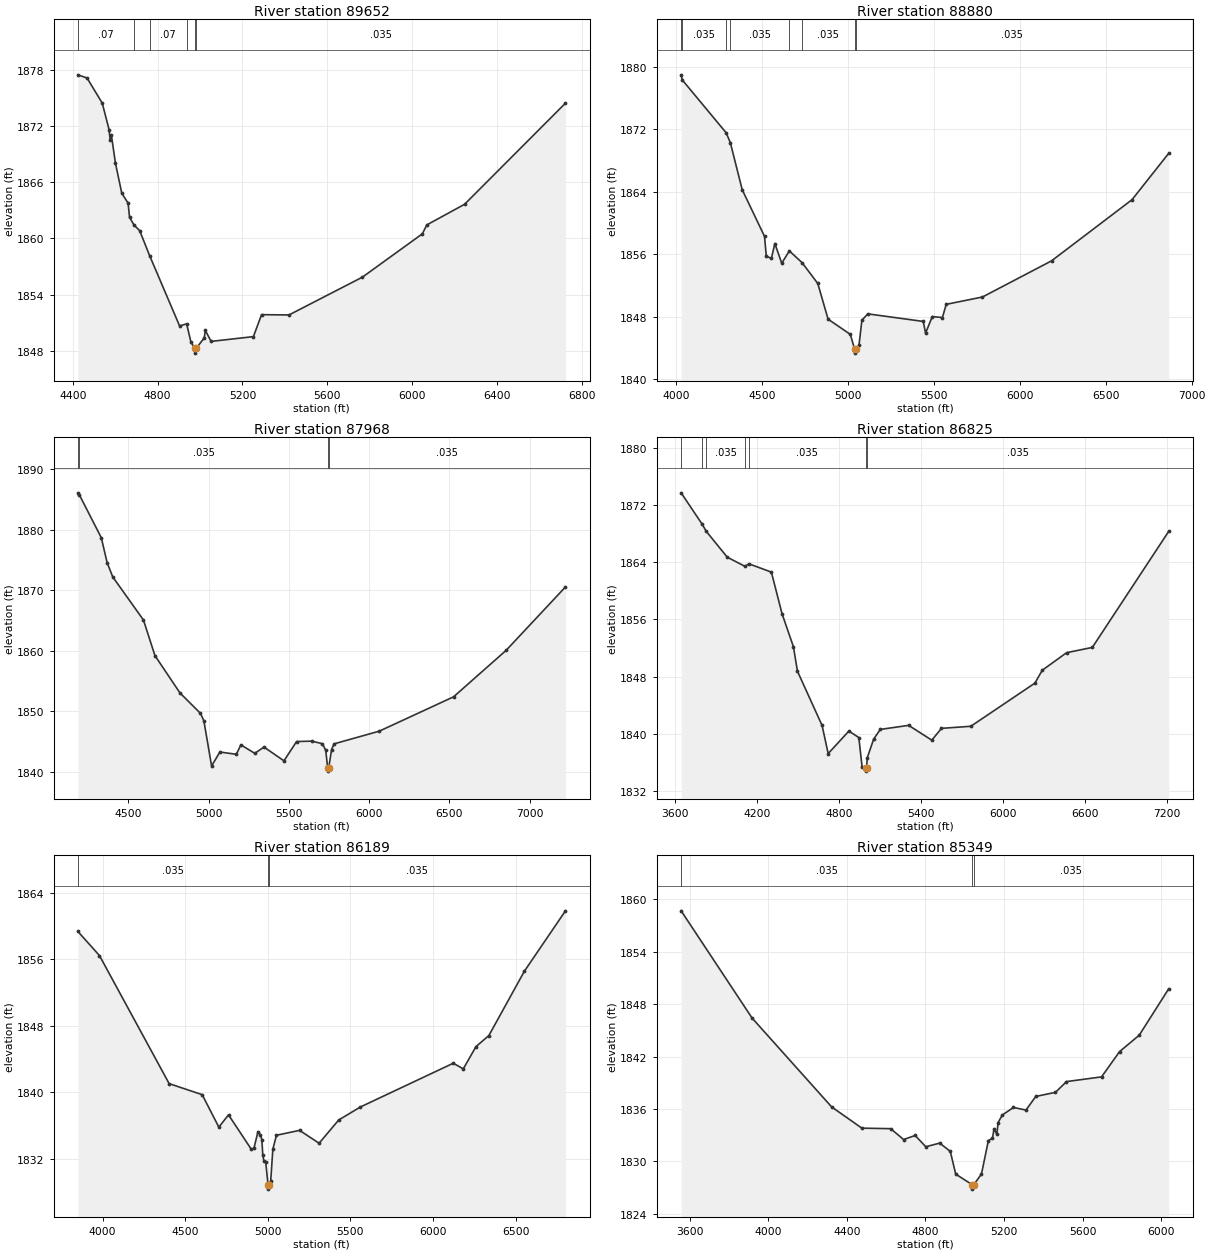
Type RM Length L Ch R = 1,89652,772,772,772
BEGIN DESCRIPTION:
Mapping XS 04167171
END DESCRIPTION:
XS GIS Cut Line= 3
      1675795.06      6936551.15      1676003.38      6937089.31
      1676517.28      6938731.71
#Sta/Elev= 30
  4424.4 1877.44  4467.5 1877.10  4539.0 1874.43  4571.1 1871.61  4576.6 1870.48
  4581.9 1871.05  4601.1 1868.04  4631.1 1864.82  4661.0 1863.76  4667.7 1862.25
  4688.8 1861.43  4715.5 1860.83  4762.4 1858.16  4903.6 1850.67  4936.9 1850.89
  4957.2 1848.94  4975.7 1848.27  4976.2 1847.77  4981.5 1848.27  5019.7 1849.39
  5025.0 1850.19  5052.2 1849.02  5251.6 1849.53  5289.9 1851.87  5419.2 1851.84
  5765.3 1855.87  6047.9 1860.49  6068.9 1861.44  6247.0 1863.64  6722.4 1874.42
#Mann=6,-1,0
  4424.4    0.07       0  4688.8   0.035       0  4762.4    0.07       0
  4936.9   0.035       0  4975.7   0.035       0  4981.5   0.035       0
Bank Sta=4975.7,4981.5
Exp/Cntr=0.3,0.1

Type RM Length L Ch R = 1,88880,912,912,912
BEGIN DESCRIPTION:
Mapping XS cc7ab871
END DESCRIPTION:
XS GIS Cut Line= 3
      1675297.65      6936062.41      1675306.33      6937043.30
      1676126.63      6938709.94
#Sta/Elev= 30
  4027.7 1878.97  4033.8 1878.33  4290.1 1871.54  4314.3 1870.27  4383.3 1864.25
  4513.3 1858.27  4523.3 1855.76  4553.3 1855.45  4573.3 1857.36  4613.3 1854.84
  4657.8 1856.41  4731.9 1854.91  4823.3 1852.24  4883.3 1847.67  5012.8 1845.72
  5037.7 1843.82  5038.2 1843.32  5043.6 1843.82  5063.1 1844.30  5080.0 1847.52
  5114.2 1848.35  5437.4 1847.38  5450.7 1845.88  5490.0 1848.00  5548.9 1847.88
  5571.1 1849.57  5782.1 1850.51  6184.2 1855.14  6652.6 1862.97  6866.2 1868.91
#Mann=8,-1,0
  4027.7    0.07       0  4033.8   0.035       0  4290.1    0.07       0
  4314.3   0.035       0  4657.8    0.07       0  4731.9   0.035       0
  5037.7   0.035       0  5043.6   0.035       0
Bank Sta=5037.7,5043.6
Exp/Cntr=0.3,0.1

Type RM Length L Ch R = 1,87968,1143,1143,1143
BEGIN DESCRIPTION:
Mapping XS 4d1616e7
END DESCRIPTION:
XS GIS Cut Line= 3
      1674038.94      6936418.27      1674577.16      6937056.32
      1675766.41      6938909.63
#Sta/Elev= 30
  4186.0 1886.08  4194.8 1885.76  4331.7 1878.67  4368.0 1874.55  4403.1 1872.20
  4594.3 1865.09  4665.8 1859.22  4821.8 1853.06  4949.3 1849.69  4970.6 1848.46
  5018.6 1841.01  5070.3 1843.31  5172.7 1842.94  5201.0 1844.49  5287.6 1843.10
  5345.1 1844.13  5469.3 1841.86  5548.0 1845.04  5641.8 1845.11  5708.5 1844.69
  5729.7 1843.59  5741.7 1840.66  5742.2 1840.16  5748.0 1840.66  5766.0 1843.72
  5781.2 1844.66  6062.6 1846.75  6525.8 1852.42  6852.5 1860.07  7222.8 1870.55
#Mann=4,-1,0
  4186.0    0.07       0  4194.8   0.035       0  5741.7   0.035       0
  5748.0   0.035       0
Bank Sta=5741.7,5748
Exp/Cntr=0.3,0.1

Type RM Length L Ch R = 1,86825,636,636,636
BEGIN DESCRIPTION:
Mapping XS 18fef6d5
END DESCRIPTION:
XS GIS Cut Line= 3
      1673644.01      6936440.01      1674151.82      6937703.02
      1674794.18      6939812.41
#Sta/Elev= 30
  3646.2 1873.76  3801.3 1869.32  3829.2 1868.38  3983.7 1864.73  4112.4 1863.46
  4142.3 1863.80  4306.3 1862.64  4384.2 1856.81  4467.5 1852.18  4497.1 1848.74
  4677.1 1841.14  4721.8 1837.19  4873.3 1840.35  4945.9 1839.44  4969.7 1835.37
  4996.3 1835.23  4996.8 1834.73  5002.9 1835.23  5007.5 1836.59  5054.5 1839.22
  5102.9 1840.58  5310.4 1841.15  5479.8 1839.07  5550.7 1840.73  5765.3 1841.02
  6233.8 1847.07  6288.0 1848.88  6465.7 1851.34  6654.0 1852.08  7212.5 1868.35
#Mann=7,-1,0
  3646.2   0.035       0  3801.3    0.07       0  3829.2   0.035       0
  4112.4    0.07       0  4142.3   0.035       0  4996.3   0.035       0
  5002.9   0.035       0
Bank Sta=4996.3,5002.9
Exp/Cntr=0.3,0.1

Type RM Length L Ch R = 1,86189,840,840,840
BEGIN DESCRIPTION:
Mapping XS ef9abb0e
END DESCRIPTION:
XS GIS Cut Line= 3
      1673192.04      6936947.82      1673634.74      6938015.52
      1674303.13      6939682.15
#Sta/Elev= 30
  3850.4 1859.37  3980.8 1856.47  4402.7 1841.04  4602.6 1839.71  4703.5 1835.80
  4762.1 1837.28  4900.7 1833.11  4916.2 1833.27  4940.1 1835.23  4954.8 1834.88
  4964.0 1834.28  4969.4 1832.49  4976.4 1831.66  4987.3 1831.58  5001.5 1828.83
  5002.0 1828.33  5008.2 1828.83  5017.3 1829.25  5030.5 1833.15  5052.3 1834.82
  5192.1 1835.41  5310.5 1833.86  5429.1 1836.66  5560.7 1838.23  6122.9 1843.50
  6183.3 1842.82  6260.1 1845.50  6338.1 1846.83  6553.4 1854.59  6801.9 1861.86
#Mann=3,-1,0
  3850.4   0.035       0  5001.5   0.035       0  5008.2   0.035       0
Bank Sta=5001.5,5008.2
Exp/Cntr=0.3,0.1

Type RM Length L Ch R = 1,85349,243,243,243
BEGIN DESCRIPTION:
Mapping XS c6072aad
END DESCRIPTION:
XS GIS Cut Line= 3
      1672624.34      6937458.26      1673327.45      6938726.46
      1673983.72      6939520.75
#Sta/Elev= 30
  3557.4 1858.68  3918.5 1846.40  4323.2 1836.23  4477.0 1833.80  4623.5 1833.74
  4689.1 1832.50  4748.3 1832.96  4802.1 1831.67  4873.0 1832.09  4926.8 1831.14
  4954.3 1828.54  5038.7 1827.32  5039.2 1826.82  5046.1 1827.32  5085.4 1828.55
  5120.5 1832.38  5141.4 1832.64  5149.2 1833.72  5163.6 1833.10  5170.0 1834.44
  5191.1 1835.30  5248.2 1836.17  5312.0 1835.87  5361.5 1837.43  5461.9 1837.90
  5517.9 1839.13  5696.4 1839.67  5787.8 1842.56  5887.9 1844.44  6037.8 1849.75
#Mann=3,-1,0
  3557.4   0.035       0  5038.7   0.035       0  5046.1   0.035       0
Bank Sta=5038.7,5046.1
Exp/Cntr=0.3,0.1

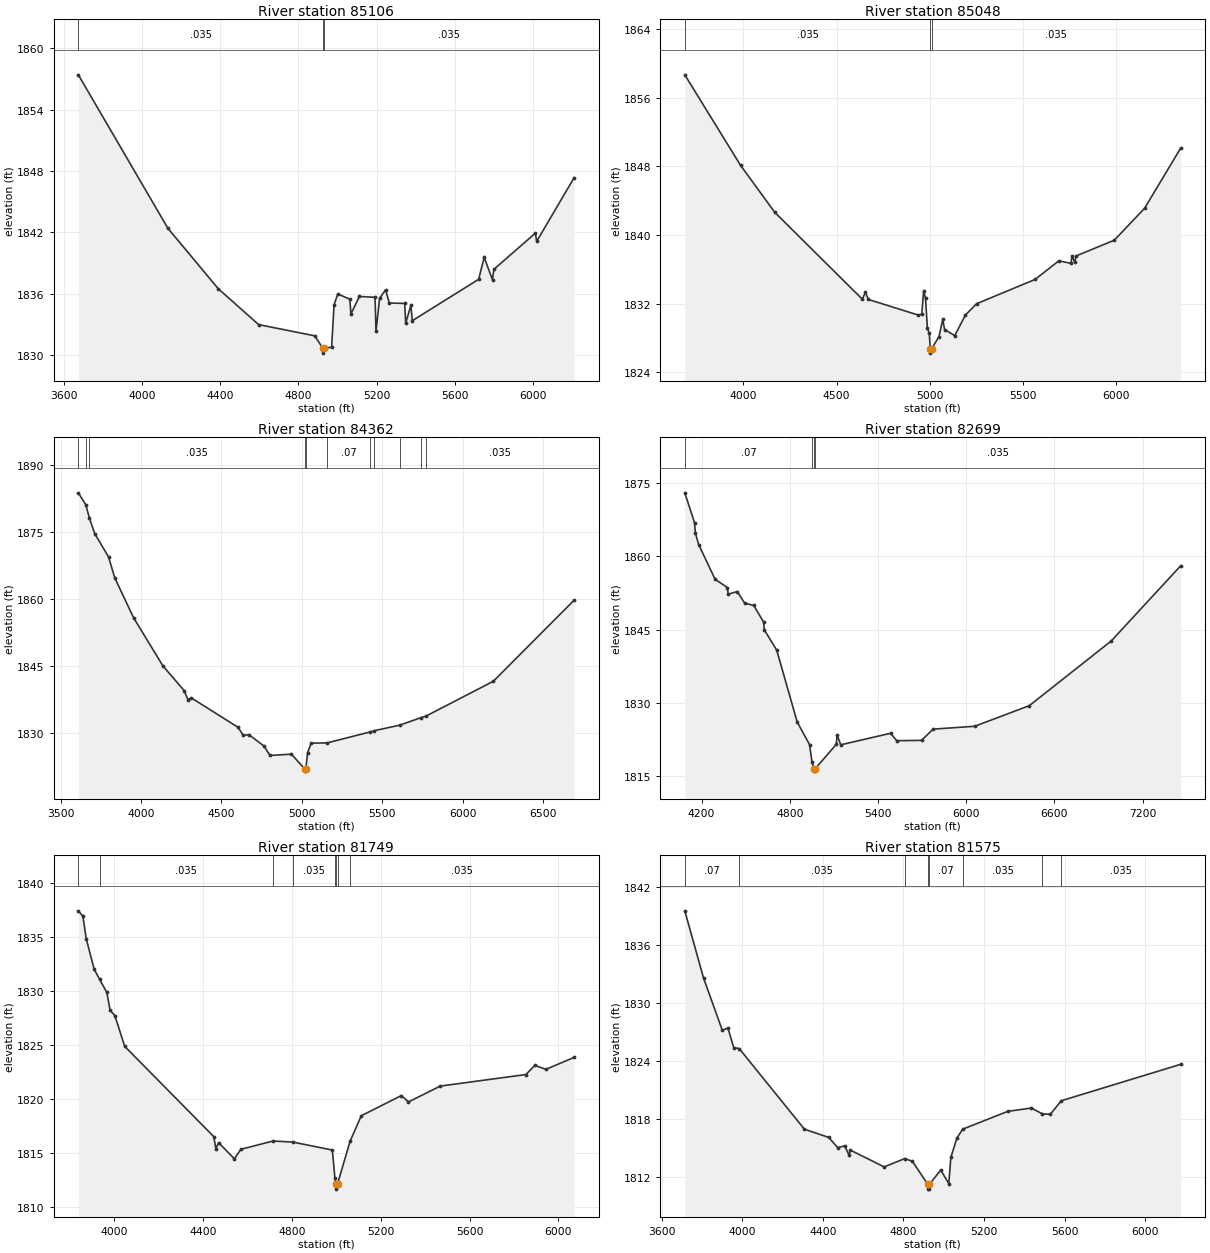
Type RM Length L Ch R = 1,85106,58,58,58
BEGIN DESCRIPTION:
Mapping XS e6999737
END DESCRIPTION:
XS GIS Cut Line= 6
      1672593.10      6937523.38      1673184.22      6938632.71
      1673126.93      6938791.56      1673158.18      6938872.29
      1673335.27      6938895.73      1673915.97      6939507.69
#Sta/Elev= 30
  3673.9 1857.41  4132.2 1842.40  4389.6 1836.50  4596.0 1832.99  4883.6 1831.89
  4923.5 1830.70  4924.0 1830.20  4930.9 1830.70  4969.5 1830.77  4982.1 1834.93
  5001.0 1835.99  5062.8 1835.47  5068.2 1834.03  5111.8 1835.74  5191.6 1835.66
  5196.6 1832.35  5215.0 1835.56  5245.3 1836.38  5265.0 1835.10  5343.4 1835.06
  5348.5 1833.14  5375.0 1834.87  5382.3 1833.37  5721.7 1837.42  5750.0 1839.57
  5792.5 1837.36  5799.4 1838.39  6011.7 1841.93  6018.6 1841.13  6210.2 1847.36
#Mann=3,-1,0
  3673.9   0.035       0  4923.5   0.035       0  4930.9   0.035       0
Bank Sta=4923.5,4930.9
Exp/Cntr=0.3,0.1

Type RM Length L Ch R = 1,85048,686,686,686
BEGIN DESCRIPTION:
Mapping XS 8642e27f
END DESCRIPTION:
XS GIS Cut Line= 6
      1672546.22      6937518.16      1673074.85      6938458.23
      1673077.45      6938820.21      1673134.74      6938955.63
      1673306.62      6938968.65      1673944.66      6939591.06
#Sta/Elev= 30
  3686.6 1858.65  3985.2 1848.12  4168.8 1842.64  4638.6 1832.52  4654.5 1833.35
  4670.5 1832.50  4936.5 1830.69  4956.7 1830.77  4966.8 1833.53  4976.9 1832.61
  4987.0 1829.16  4997.1 1828.55  5002.2 1826.75  5002.7 1826.25  5009.6 1826.75
  5048.9 1828.17  5069.2 1830.18  5079.0 1829.00  5133.5 1828.29  5191.0 1830.69
  5250.5 1832.00  5564.3 1834.83  5691.6 1837.00  5755.4 1836.70  5762.4 1837.52
  5776.5 1836.83  5783.7 1837.56  5988.7 1839.40  6151.3 1843.12  6344.2 1850.11
#Mann=3,-1,0
  3686.6   0.035       0  5002.2   0.035       0  5009.6   0.035       0
Bank Sta=5002.2,5009.6
Exp/Cntr=0.3,0.1

Type RM Length L Ch R = 1,84362,1663,1663,1663
BEGIN DESCRIPTION:
Mapping XS bcc6fae6
END DESCRIPTION:
XS GIS Cut Line= 3
      1671364.77      6938380.10      1672571.38      6939074.55
      1673899.54      6940120.58
#Sta/Elev= 30
  3609.9 1883.86  3655.8 1881.23  3678.9 1878.17  3712.1 1874.71  3798.3 1869.47
  3835.7 1864.87  3953.5 1855.87  4136.0 1845.08  4267.8 1839.56  4290.9 1837.56
  4312.8 1837.92  4603.1 1831.33  4634.7 1829.57  4671.7 1829.64  4764.1 1827.15
  4801.4 1825.03  4935.0 1825.32  5017.0 1822.02  5017.5 1821.52  5024.5 1822.02
  5035.2 1825.61  5057.6 1827.79  5156.1 1827.84  5425.5 1830.31  5448.7 1830.57
  5607.4 1831.81  5742.1 1833.52  5771.1 1833.84  6189.9 1841.64  6692.7 1859.82
#Mann=11,-1,0
  3609.9   0.035       0  3655.8    0.07       0  3678.9   0.035       0
  5017.0   0.035       0  5024.5   0.035       0  5156.1    0.07       0
  5425.5   0.035       0  5448.7    0.07       0  5607.4   0.035       0
  5742.1    0.07       0  5771.1   0.035       0
Bank Sta=5017,5024.5
Exp/Cntr=0.3,0.1

Type RM Length L Ch R = 1,82699,950,950,950
BEGIN DESCRIPTION:
Mapping XS 6dd6b1d2
END DESCRIPTION:
XS GIS Cut Line= 3
      1670565.48      6939050.91      1671382.78      6939460.31
      1673674.41      6940350.06
#Sta/Elev= 30
  4086.1 1873.04  4152.4 1866.92  4158.0 1864.81  4180.4 1862.44  4292.1 1855.34
  4375.9 1853.63  4381.5 1852.27  4442.9 1852.83  4493.2 1850.45  4554.7 1849.97
  4621.7 1846.59  4627.3 1844.95  4711.1 1840.83  4850.8 1826.09  4934.6 1821.48
  4951.8 1817.81  4965.1 1816.54  4965.6 1816.04  4973.2 1816.54  5116.7 1821.53
  5122.0 1823.47  5146.6 1821.43  5485.3 1823.79  5527.7 1822.27  5696.4 1822.34
  5774.9 1824.64  6058.4 1825.23  6429.3 1829.45  6987.1 1842.71  7458.5 1858.09
#Mann=4,-1,0
  4086.1    0.07       0  4951.8   0.035       0  4965.1   0.035       0
  4973.2   0.035       0
Bank Sta=4965.1,4973.2
Exp/Cntr=0.3,0.1

Type RM Length L Ch R = 1,81749,174,174,174
BEGIN DESCRIPTION:
Mapping XS 8b35b038
END DESCRIPTION:
XS GIS Cut Line= 4
      1670228.94      6939485.12      1670621.47      6940063.12
      1671088.74      6940111.40      1672151.91      6940184.18
#Sta/Elev= 30
  3837.3 1837.43  3857.9 1836.94  3872.9 1834.84  3908.8 1832.01  3933.5 1831.07
  3965.7 1829.87  3980.7 1828.20  4001.7 1827.73  4046.3 1824.87  4447.8 1816.50
  4456.7 1815.39  4469.4 1815.95  4540.3 1814.45  4569.7 1815.33  4714.7 1816.10
  4803.7 1816.00  4981.9 1815.26  4993.6 1812.63  4997.3 1812.14  4997.8 1811.64
  5005.4 1812.14  5062.2 1816.10  5112.3 1818.44  5292.7 1820.31  5324.9 1819.72
  5468.3 1821.19  5854.0 1822.26  5894.1 1823.11  5944.2 1822.74  6071.4 1823.85
#Mann=8,-1,0
  3837.3    0.07       0  3933.5   0.035       0  4714.7    0.07       0
  4803.7   0.035       0  4993.6    0.07       0  4997.3    0.07       0
  5005.4    0.07       0  5062.2   0.035       0
Bank Sta=4997.3,5005.4
Exp/Cntr=0.3,0.1

Type RM Length L Ch R = 1,81575,708,708,708
BEGIN DESCRIPTION:
Mapping XS c50e186f
END DESCRIPTION:
XS GIS Cut Line= 4
      1670034.50      6939488.60      1670565.35      6940201.52
      1670961.13      6940233.79      1672127.75      6940366.60
#Sta/Elev= 30
  3715.6 1839.57  3808.4 1832.63  3901.9 1827.20  3929.4 1827.45  3958.6 1825.42
  3985.6 1825.32  4309.0 1816.98  4429.9 1816.13  4473.7 1815.08  4509.2 1815.25
  4530.0 1814.31  4537.7 1814.81  4704.4 1813.08  4807.2 1813.94  4844.9 1813.66
  4921.1 1811.28  4921.6 1810.78  4928.7 1810.78  4929.2 1811.28  4985.4 1812.75
  5025.6 1811.35  5035.6 1814.06  5065.8 1816.06  5094.4 1816.98  5317.4 1818.82
  5434.9 1819.17  5489.6 1818.57  5529.4 1818.52  5583.3 1819.92  6175.7 1823.69
#Mann=8,-1,0
  3715.6    0.07       0  3985.6   0.035       0  4807.2    0.07       0
  4921.1    0.07       0  4929.2    0.07       0  5094.4   0.035       0
  5489.6    0.07       0  5583.3   0.035       0
Bank Sta=4921.1,4929.2
Exp/Cntr=0.3,0.1

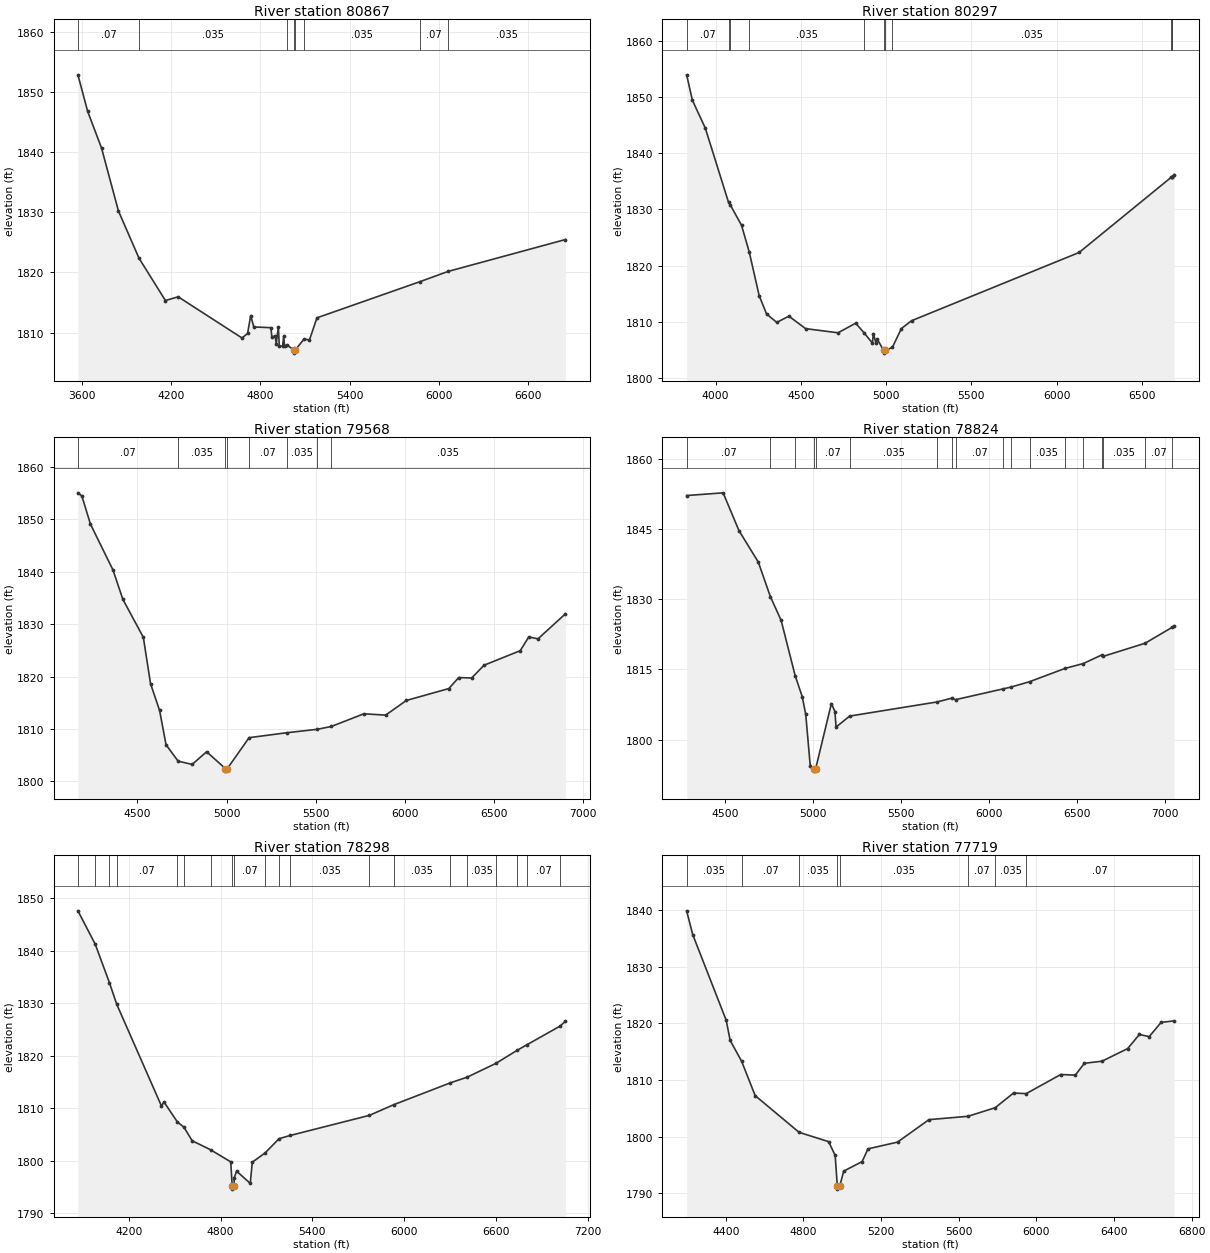
Type RM Length L Ch R = 1,80867,570,570,570
BEGIN DESCRIPTION:
Mapping XS 56242b2f
END DESCRIPTION:
XS GIS Cut Line= 3
      1669611.62      6939460.09      1670455.92      6940608.79
      1672300.55      6940499.08
#Sta/Elev= 30
  3575.7 1852.92  3640.9 1846.85  3734.4 1840.72  3847.7 1830.25  3986.1 1822.37
  4163.3 1815.33  4248.9 1815.95  4677.6 1809.09  4714.9 1809.84  4735.8 1812.81
  4756.6 1810.93  4871.6 1810.81  4877.8 1809.26  4900.9 1809.43  4907.1 1808.12
  4921.7 1810.90  4927.9 1807.68  4950.7 1807.78  4957.2 1809.37  4963.4 1807.77
  4982.6 1807.89  5026.2 1807.07  5026.7 1806.57  5034.7 1807.07  5093.8 1808.91
  5130.6 1808.77  5180.7 1812.45  5870.0 1818.45  6061.6 1820.18  6849.2 1825.49
#Mann=8,-1,0
  3575.7    0.07       0  3986.1   0.035       0  4982.6    0.07       0
  5026.2    0.07       0  5034.7    0.07       0  5093.8   0.035       0
  5870.0    0.07       0  6061.6   0.035       0
Bank Sta=5026.2,5034.7
Exp/Cntr=0.3,0.1

Type RM Length L Ch R = 1,80297,729,729,729
BEGIN DESCRIPTION:
Mapping XS bd749dd7
END DESCRIPTION:
XS GIS Cut Line= 3
      1669524.83      6939612.02      1670084.74      6940636.34
      1670206.20      6942323.82
#Sta/Elev= 30
  3830.5 1853.96  3864.0 1849.45  3939.8 1844.49  4076.1 1831.28  4086.1 1830.84
  4152.4 1827.19  4198.2 1822.37  4255.8 1814.68  4299.4 1811.40  4359.2 1809.91
  4430.3 1811.02  4528.0 1808.80  4718.7 1808.06  4822.1 1809.77  4871.1 1808.05
  4919.9 1806.23  4925.6 1807.92  4941.7 1806.16  4947.4 1807.01  4985.2 1804.94
  4985.7 1804.44  4996.8 1804.94  5037.1 1805.46  5089.8 1808.81  5149.9 1810.21
  6132.4 1822.35  6671.4 1835.70  6675.2 1835.77  6677.8 1835.82  6689.7 1836.21
#Mann=11,-1,0
  3830.5    0.07       0  4076.1   0.035       0  4086.1    0.07       0
  4198.2   0.035       0  4871.1    0.07       0  4985.2    0.07       0
  4996.8    0.07       0  5037.1   0.035       0  6671.4    0.07       0
  6675.2   0.035       0  6677.8    0.07       0
Bank Sta=4985.2,4996.8
Exp/Cntr=0.3,0.1

Type RM Length L Ch R = 1,79568,744,744,744
BEGIN DESCRIPTION:
Mapping XS b5bdee5d
END DESCRIPTION:
XS GIS Cut Line= 3
      1669307.83      6939616.42      1669446.72      6940441.03
      1669924.14      6942276.94
#Sta/Elev= 30
  4166.4 1855.05  4188.3 1854.47  4236.8 1849.07  4362.9 1840.34  4418.4 1834.73
  4533.1 1827.50  4573.6 1818.64  4624.3 1813.54  4660.5 1807.00  4728.0 1803.88
  4806.9 1803.25  4888.0 1805.67  4992.8 1802.47  4993.3 1801.97  5004.4 1802.47
  5126.0 1808.35  5336.7 1809.29  5508.9 1809.95  5587.6 1810.49  5769.9 1812.91
  5891.5 1812.65  6008.0 1815.45  6246.0 1817.72  6301.4 1819.82  6373.7 1819.73
  6443.5 1822.17  6646.1 1824.94  6694.0 1827.56  6745.7 1827.20  6899.6 1831.97
#Mann=8,-1,0
  4166.4    0.07       0  4728.0   0.035       0  4992.8   0.035       0
  5004.4   0.035       0  5126.0    0.07       0  5336.7   0.035       0
  5508.9    0.07       0  5587.6   0.035       0
Bank Sta=4992.8,5004.4
Exp/Cntr=0.3,0.1

Type RM Length L Ch R = 1,78824,526,526,526
BEGIN DESCRIPTION:
Mapping XS ae49cf20
END DESCRIPTION:
XS GIS Cut Line= 3
      1668935.43      6939420.45      1668909.39      6940140.97
      1669547.23      6942093.54
#Sta/Elev= 30
  4279.2 1852.22  4486.9 1852.80  4576.9 1844.73  4687.0 1837.99  4755.8 1830.60
  4817.1 1825.51  4897.3 1813.63  4937.2 1809.20  4957.2 1805.39  4982.8 1794.42
  5001.7 1793.75  5002.2 1793.25  5013.5 1793.75  5103.2 1807.71  5123.3 1806.00
  5129.8 1802.67  5207.1 1805.03  5706.1 1808.06  5787.8 1808.86  5810.0 1808.54
  6081.8 1810.86  6126.0 1811.24  6231.0 1812.38  6433.2 1815.23  6537.1 1816.27
  6641.0 1818.09  6651.4 1817.82  6888.6 1820.61  7042.4 1824.01  7054.3 1824.35
#Mann=18,-1,0
  4279.2    0.07       0  4755.8   0.035       0  4897.3    0.07       0
  5001.7    0.07       0  5013.5    0.07       0  5207.1   0.035       0
  5706.1    0.07       0  5787.8   0.035       0  5810.0    0.07       0
  6081.8   0.035       0  6126.0    0.07       0  6231.0   0.035       0
  6433.2    0.07       0  6537.1   0.035       0  6641.0    0.07       0
  6651.4   0.035       0  6888.6    0.07       0  7042.4   0.035       0
Bank Sta=5001.7,5013.5
Exp/Cntr=0.3,0.1

Type RM Length L Ch R = 1,78298,579,579,579
BEGIN DESCRIPTION:
Mapping XS 72645d3d
END DESCRIPTION:
XS GIS Cut Line= 3
      1667984.90      6939424.80      1668497.06      6940444.79
      1669356.42      6942302.39
#Sta/Elev= 30
  3867.5 1847.55  3980.9 1841.19  4073.8 1833.86  4121.7 1829.76  4413.7 1810.44
  4430.5 1811.20  4517.9 1807.40  4560.6 1806.42  4614.7 1803.83  4734.7 1802.12
  4867.0 1799.81  4876.7 1795.13  4877.2 1794.63  4888.8 1795.13  4889.4 1796.76
  4905.1 1798.05  4994.4 1795.72  5007.9 1799.75  5092.1 1801.52  5182.4 1804.22
  5256.8 1804.84  5773.9 1808.66  5933.2 1810.69  6304.0 1814.85  6413.0 1815.92
  6600.8 1818.54  6740.0 1821.03  6806.1 1822.12  7021.7 1825.65  7055.6 1826.57
#Mann=20,-1,0
  3867.5   0.035       0  3980.9    0.07       0  4073.8   0.035       0
  4121.7    0.07       0  4517.9   0.035       0  4560.6    0.07       0
  4734.7   0.035       0  4876.7    0.07       0  4888.8    0.07       0
  5092.1   0.035       0  5182.4    0.07       0  5256.8   0.035       0
  5773.9    0.07       0  5933.2   0.035       0  6304.0    0.07       0
  6413.0   0.035       0  6600.8    0.07       0  6740.0   0.035       0
  6806.1    0.07       0  7021.7   0.035       0
Bank Sta=4876.7,4888.8
Exp/Cntr=0.3,0.1

Type RM Length L Ch R = 1,77719,516,516,516
BEGIN DESCRIPTION:
Mapping XS 4be81c2f
END DESCRIPTION:
XS GIS Cut Line= 3
      1667809.16      6939647.07      1667948.05      6940445.69
      1668222.10      6942124.67
#Sta/Elev= 30
  4198.0 1839.88  4229.4 1835.68  4401.9 1820.55  4422.2 1817.00  4480.9 1813.35
  4551.1 1807.25  4777.4 1800.77  4929.7 1799.12  4963.4 1796.68  4974.4 1791.24
  4974.9 1790.74  4986.6 1791.24  5007.2 1793.92  5102.1 1795.60  5132.5 1797.85
  5284.5 1799.04  5446.6 1803.01  5647.9 1803.60  5788.0 1805.12  5882.3 1807.71
  5947.4 1807.60  6125.5 1810.98  6200.8 1810.87  6247.1 1812.96  6338.3 1813.33
  6470.0 1815.55  6530.8 1818.05  6581.5 1817.67  6642.2 1820.17  6709.8 1820.45
#Mann=8,-1,0
  4198.0   0.035       0  4480.9    0.07       0  4777.4   0.035       0
  4974.4   0.035       0  4986.6   0.035       0  5647.9    0.07       0
  5788.0   0.035       0  5947.4    0.07       0
Bank Sta=4974.4,4986.6
Exp/Cntr=0.3,0.1

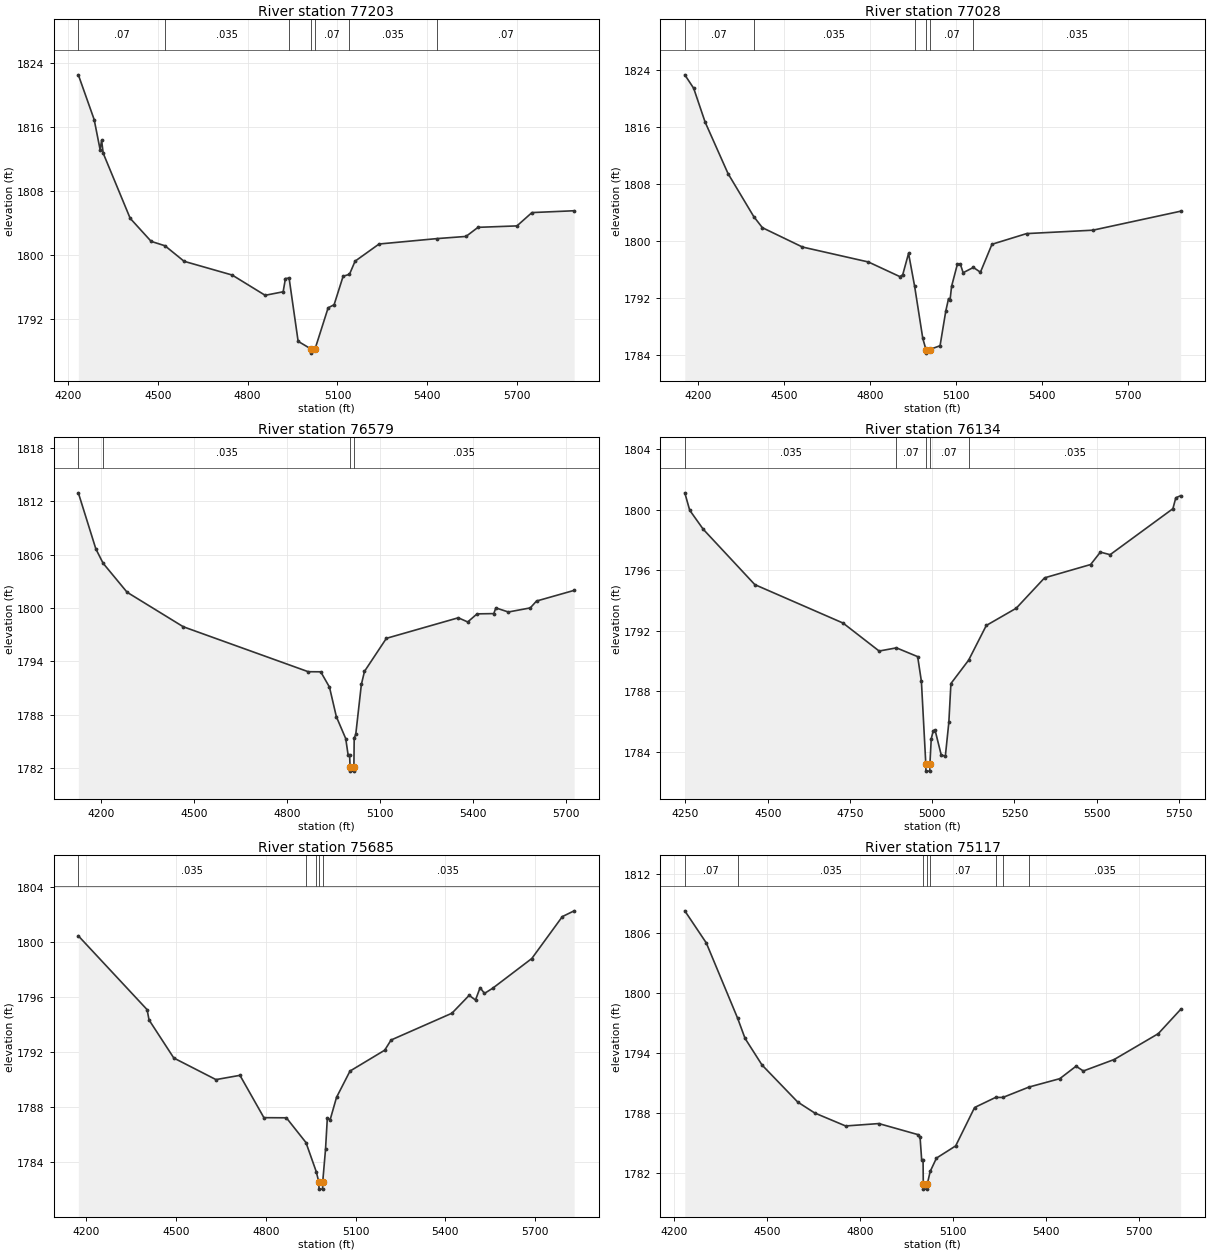
Type RM Length L Ch R = 1,77203,175,175,175
BEGIN DESCRIPTION:
Mapping XS 59095213
END DESCRIPTION:
XS GIS Cut Line= 3
      1667545.03      6939885.21      1667495.12      6940653.40
      1667449.54      6941538.82
#Sta/Elev= 30
  4234.4 1822.57  4287.3 1816.96  4307.1 1813.20  4312.2 1814.35  4317.4 1812.75
  4407.6 1804.58  4477.7 1801.69  4523.8 1801.14  4587.9 1799.19  4748.3 1797.47
  4858.5 1794.93  4918.6 1795.37  4926.3 1797.03  4938.5 1797.09  4968.7 1789.16
  5012.6 1788.18  5013.1 1787.68  5025.0 1788.18  5068.9 1793.36  5088.9 1793.75
  5119.0 1797.32  5140.2 1797.56  5159.0 1799.21  5239.1 1801.36  5433.1 1802.04
  5529.5 1802.31  5569.6 1803.45  5699.7 1803.63  5749.8 1805.30  5890.8 1805.53
#Mann=7,-1,0
  4234.4    0.07       0  4523.8   0.035       0  4938.5    0.07       0
  5012.6    0.07       0  5025.0    0.07       0  5140.2   0.035       0
  5433.1    0.07       0
Bank Sta=5012.6,5025
Exp/Cntr=0.3,0.1

Type RM Length L Ch R = 1,77028,449,449,449
BEGIN DESCRIPTION:
Mapping XS 302805c9
END DESCRIPTION:
XS GIS Cut Line= 3
      1667351.89      6939857.00      1667338.87      6940707.65
      1667234.70      6941582.22
#Sta/Elev= 30
  4153.0 1823.34  4184.0 1821.45  4224.0 1816.69  4304.0 1809.45  4393.7 1803.41
  4424.0 1801.84  4564.0 1799.12  4794.1 1797.02  4904.1 1794.96  4914.1 1795.23
  4934.4 1798.23  4955.6 1793.60  4984.1 1786.27  4995.2 1784.70  4995.7 1784.20
  5007.6 1784.70  5044.4 1785.24  5064.5 1790.14  5074.1 1791.87  5079.2 1791.64
  5084.7 1793.60  5104.8 1796.69  5114.9 1796.76  5125.0 1795.51  5160.8 1796.25
  5185.4 1795.58  5225.7 1799.51  5346.5 1801.01  5578.1 1801.49  5884.5 1804.16
#Mann=6,-1,0
  4153.0    0.07       0  4393.7   0.035       0  4955.6    0.07       0
  4995.2    0.07       0  5007.6    0.07       0  5160.8   0.035       0
Bank Sta=4995.2,5007.6
Exp/Cntr=0.3,0.1

Type RM Length L Ch R = 1,76579,445,445,445
BEGIN DESCRIPTION:
Mapping XS 38a336d1
END DESCRIPTION:
XS GIS Cut Line= 3
      1666828.88      6939971.93      1666937.39      6940837.95
      1667035.05      6941558.37
#Sta/Elev= 30
  4127.2 1812.93  4183.7 1806.63  4207.1 1805.02  4284.5 1801.76  4465.9 1797.88
  4869.0 1792.83  4909.3 1792.82  4937.5 1791.10  4959.7 1787.78  4990.0 1785.31
  4997.5 1783.51  5002.5 1783.51  5003.9 1782.16  5004.4 1781.66  5015.8 1781.66
  5016.3 1782.16  5017.3 1785.39  5022.3 1785.78  5040.4 1791.40  5050.5 1792.87
  5121.1 1796.58  5353.2 1798.89  5383.5 1798.42  5413.8 1799.33  5467.7 1799.36
  5474.3 1800.00  5514.7 1799.54  5585.4 1800.00  5605.5 1800.77  5727.0 1801.97
#Mann=4,-1,0
  4127.2    0.07       0  4207.1   0.035       0  5003.9   0.035       0
  5016.3   0.035       0
Bank Sta=5003.9,5016.3
Exp/Cntr=0.3,0.1

Type RM Length L Ch R = 1,76134,449,449,449
BEGIN DESCRIPTION:
Mapping XS 3e9617c1
END DESCRIPTION:
XS GIS Cut Line= 3
      1666325.60      6940161.53      1666510.06      6940895.01
      1666790.01      6941591.65
#Sta/Elev= 30
  4247.9 1801.11  4262.8 1799.96  4304.0 1798.70  4460.8 1795.04  4728.9 1792.50
  4838.6 1790.65  4891.2 1790.86  4955.7 1790.28  4967.1 1788.64  4980.4 1783.21
  4980.9 1782.71  4992.5 1782.71  4993.0 1783.21  4997.0 1784.85  5003.1 1785.38
  5008.5 1785.43  5027.2 1783.79  5039.8 1783.69  5050.5 1785.94  5056.8 1788.50
  5110.7 1790.05  5164.3 1792.34  5255.3 1793.48  5341.5 1795.49  5481.5 1796.37
  5511.1 1797.19  5540.7 1797.02  5731.5 1800.06  5740.3 1800.78  5755.0 1800.92
#Mann=5,-1,0
  4247.9   0.035       0  4891.2    0.07       0  4980.4    0.07       0
  4993.0    0.07       0  5110.7   0.035       0
Bank Sta=4980.4,4993
Exp/Cntr=0.3,0.1

Type RM Length L Ch R = 1,75685,568,568,568
BEGIN DESCRIPTION:
Mapping XS a0777831
END DESCRIPTION:
XS GIS Cut Line= 3
      1665911.09      6940239.58      1666125.94      6941044.75
      1666566.50      6941741.39
#Sta/Elev= 30
  4173.3 1800.47  4403.2 1795.10  4409.7 1794.35  4492.5 1791.58  4633.4 1790.01
  4713.6 1790.32  4793.7 1787.24  4868.8 1787.23  4934.3 1785.43  4968.7 1783.31
  4977.5 1782.54  4978.0 1782.04  4989.7 1782.04  4990.2 1782.54  4999.7 1784.94
  5005.7 1787.20  5015.3 1787.10  5036.5 1788.72  5081.5 1790.63  5197.6 1792.15
  5218.8 1792.89  5422.3 1794.84  5479.9 1796.14  5501.1 1795.80  5516.4 1796.70
  5531.1 1796.28  5558.7 1796.66  5689.3 1798.82  5791.4 1801.87  5830.9 1802.29
#Mann=5,-1,0
  4173.3   0.035       0  4934.3    0.07       0  4968.7   0.035       0
  4977.5   0.035       0  4990.2   0.035       0
Bank Sta=4977.5,4990.2
Exp/Cntr=0.3,0.1

Type RM Length L Ch R = 1,75117,694,694,694
BEGIN DESCRIPTION:
Mapping XS b1ec6557
END DESCRIPTION:
XS GIS Cut Line= 3
      1665300.23      6940373.15      1665573.68      6941091.51
      1665903.03      6941854.20
#Sta/Elev= 30
  4234.4 1808.26  4303.8 1805.04  4404.9 1797.49  4428.7 1795.48  4483.5 1792.81
  4598.6 1789.10  4653.5 1788.00  4753.2 1786.70  4860.2 1786.94  4988.0 1785.82
  4993.3 1785.57  4998.5 1783.30  5003.0 1783.30  5003.7 1780.87  5004.2 1780.37
  5016.1 1780.37  5016.6 1780.87  5025.9 1782.14  5046.2 1783.48  5108.1 1784.70
  5169.2 1788.55  5236.9 1789.56  5260.6 1789.56  5344.7 1790.60  5444.1 1791.44
  5496.5 1792.69  5520.0 1792.21  5619.5 1793.36  5761.7 1795.95  5833.8 1798.38
#Mann=8,-1,0
  4234.4    0.07       0  4404.9   0.035       0  5003.7   0.035       0
  5016.6   0.035       0  5025.9    0.07       0  5236.9   0.035       0
  5260.6    0.07       0  5344.7   0.035       0
Bank Sta=5003.7,5016.6
Exp/Cntr=0.3,0.1