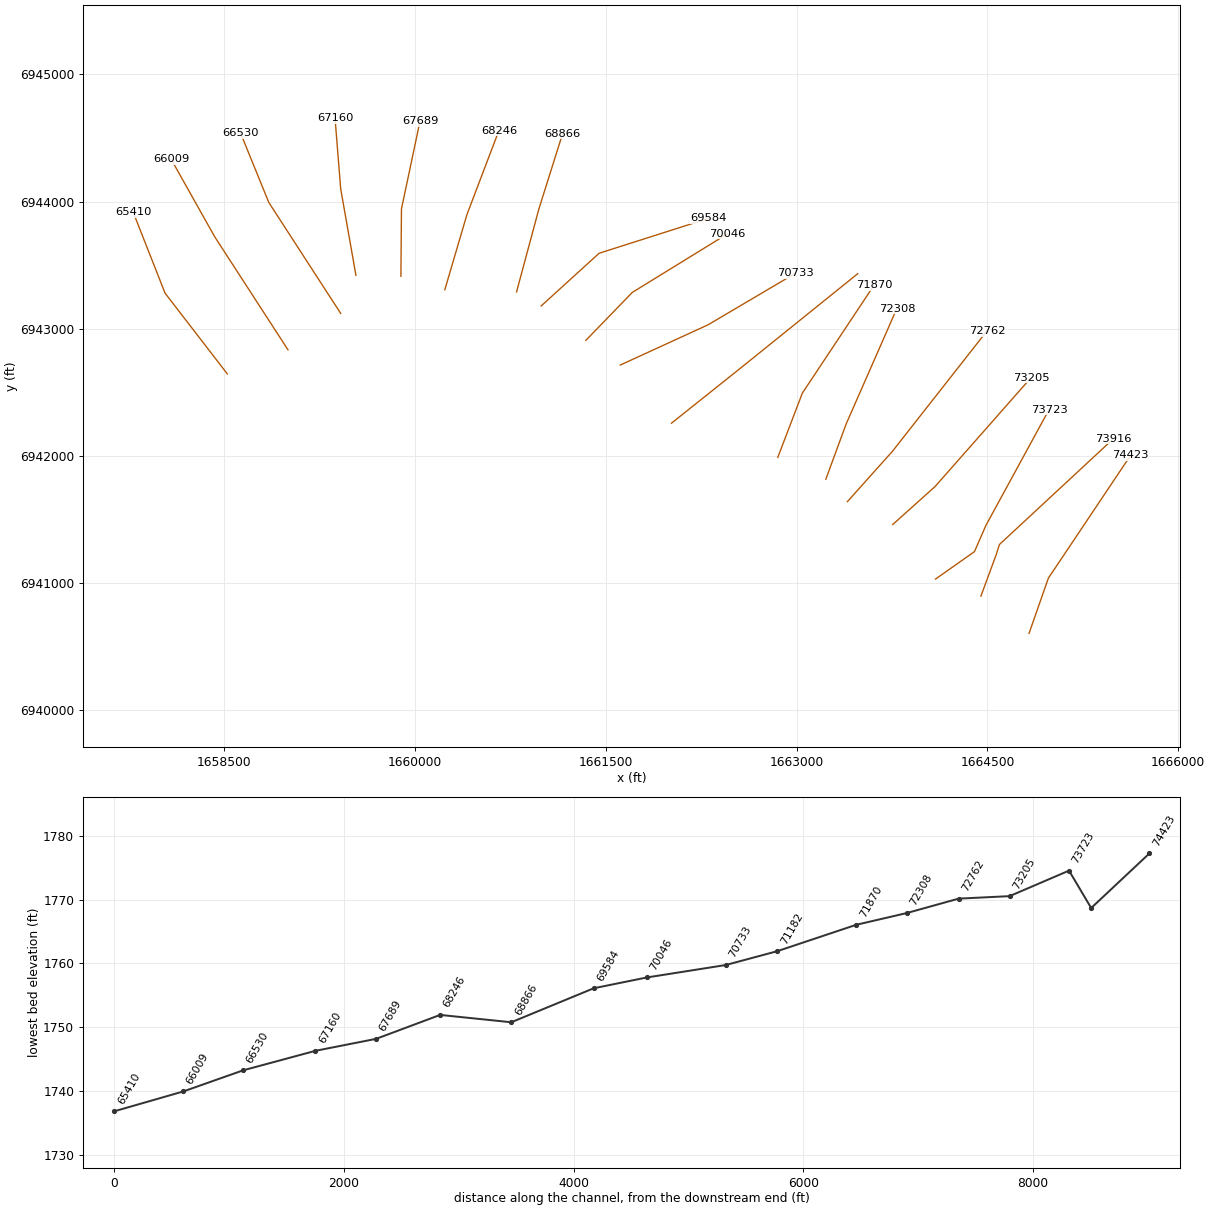
HEC-RAS study Chimney Creek.prj: Chimney Creek Base Level Engineering

--- Chimney Creek.g01 (geometry) --- (continued)

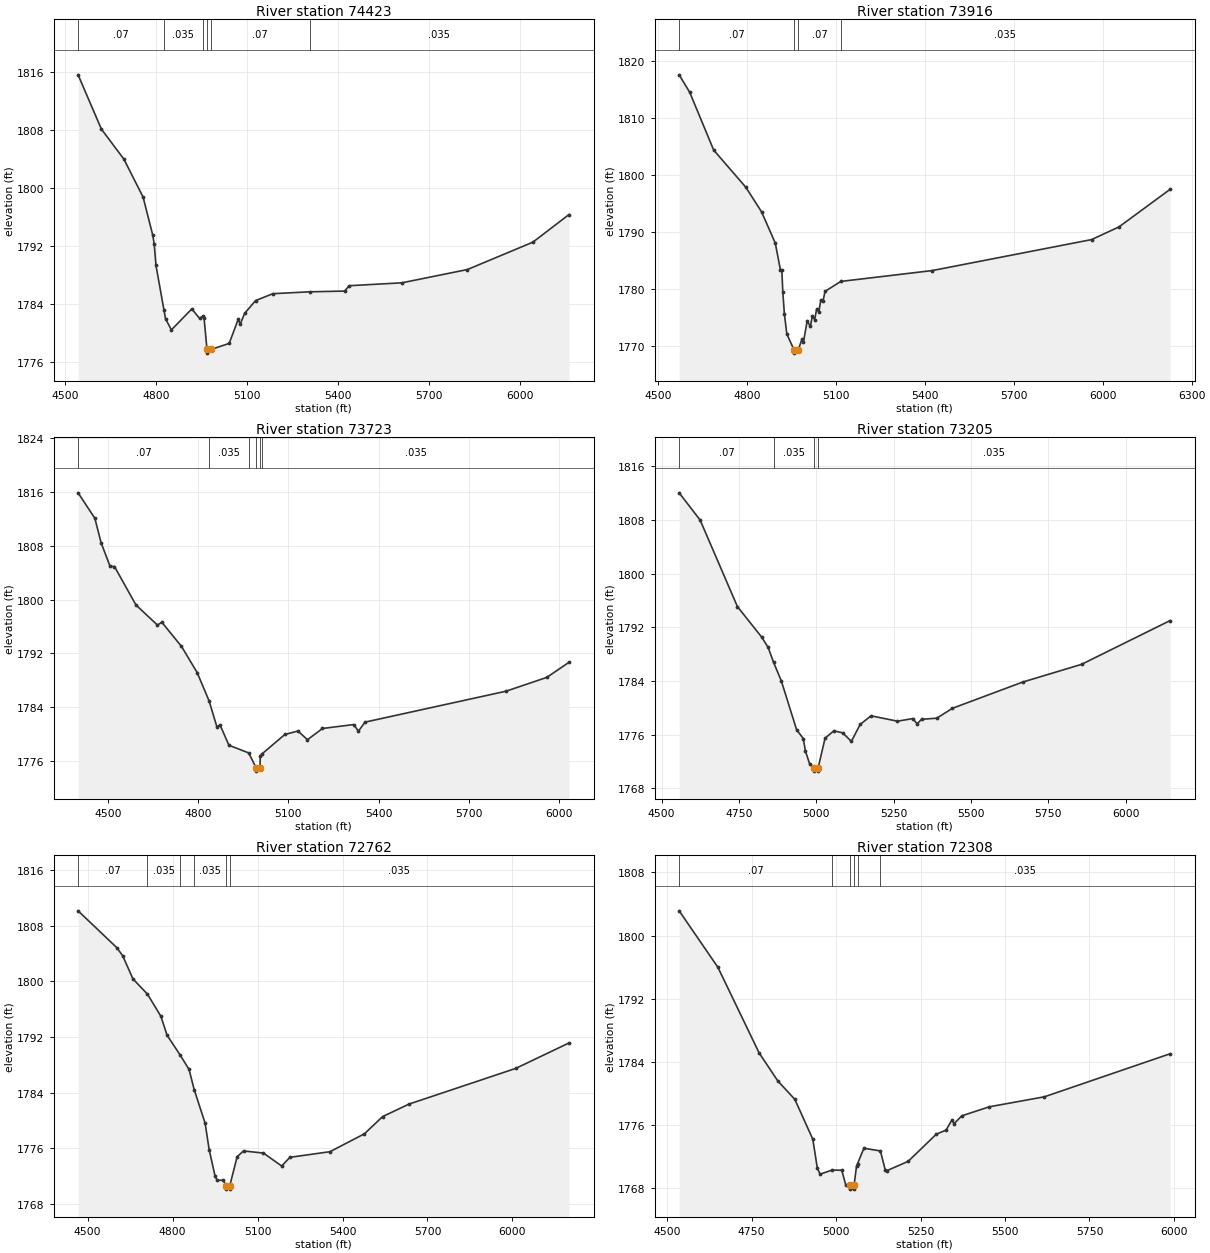
Type RM Length L Ch R = 1,74423,507,507,507
BEGIN DESCRIPTION:
Mapping XS ea27c451
END DESCRIPTION:
XS GIS Cut Line= 3
      1664827.16      6940605.39      1664979.07      6941039.42
      1665625.05      6942004.06
#Sta/Elev= 30
  4541.9 1815.59  4618.8 1808.11  4693.0 1803.98  4756.6 1798.73  4787.9 1793.58
  4793.2 1792.30  4798.9 1789.36  4825.2 1783.23  4830.7 1781.97  4849.9 1780.44
  4917.3 1783.33  4943.0 1782.03  4953.3 1782.32  4957.9 1782.05  4967.5 1777.74
  4968.0 1777.24  4980.5 1777.74  5040.8 1778.58  5070.8 1781.93  5076.8 1781.20
  5091.8 1782.72  5127.8 1784.48  5184.9 1785.43  5306.0 1785.69  5422.0 1785.79
  5437.0 1786.53  5611.1 1786.93  5827.3 1788.76  6043.4 1792.53  6162.7 1796.34
#Mann=6,-1,0
  4541.9    0.07       0  4825.2   0.035       0  4953.3    0.07       0
  4967.5    0.07       0  4980.5    0.07       0  5306.0   0.035       0
Bank Sta=4967.5,4980.5
Exp/Cntr=0.3,0.1

Type RM Length L Ch R = 1,73916,193,193,193
BEGIN DESCRIPTION:
Mapping XS 5cb80f8a
END DESCRIPTION:
XS GIS Cut Line= 4
      1664448.47      6940897.34      1664568.27      6941222.03
      1664594.31      6941303.63      1665490.91      6942136.06
#Sta/Elev= 30
  4572.1 1817.63  4607.8 1814.54  4688.4 1804.40  4796.6 1797.87  4849.9 1793.53
  4896.1 1788.04  4913.4 1783.35  4918.2 1783.35  4921.5 1779.48  4926.8 1775.58
  4935.0 1772.06  4959.9 1769.18  4960.4 1768.68  4973.0 1769.18  4985.9 1771.10
  4991.2 1770.66  5003.5 1774.26  5014.6 1773.46  5021.4 1775.27  5028.8 1774.54
  5035.6 1776.41  5043.0 1775.96  5049.8 1778.05  5057.1 1777.84  5063.9 1779.54
  5116.9 1781.29  5425.1 1783.20  5962.5 1788.65  6054.9 1790.88  6227.3 1797.49
#Mann=4,-1,0
  4572.1    0.07       0  4959.9    0.07       0  4973.0    0.07       0
  5116.9   0.035       0
Bank Sta=4959.9,4973
Exp/Cntr=0.3,0.1

Type RM Length L Ch R = 1,73723,518,518,518
BEGIN DESCRIPTION:
Mapping XS 5acef996
END DESCRIPTION:
XS GIS Cut Line= 4
      1664092.40      6941032.27      1664397.96      6941247.55
      1664488.24      6941454.15      1664983.03      6942362.14
#Sta/Elev= 30
  4400.3 1815.84  4456.1 1812.06  4477.0 1808.41  4506.6 1804.95  4521.4 1804.90
  4592.8 1799.20  4664.2 1796.22  4679.0 1796.63  4744.3 1793.05  4796.4 1789.17
  4836.0 1784.98  4861.9 1781.14  4872.8 1781.37  4902.1 1778.38  4968.0 1777.24
  4992.4 1775.04  4992.9 1774.54  5005.5 1775.04  5006.4 1776.73  5012.1 1777.09
  5088.1 1779.98  5131.8 1780.49  5163.4 1779.20  5213.4 1780.87  5316.9 1781.45
  5333.1 1780.48  5354.9 1781.81  5823.9 1786.40  5959.7 1788.45  6033.6 1790.69
#Mann=6,-1,0
  4400.3    0.07       0  4836.0   0.035       0  4968.0    0.07       0
  4992.4    0.07       0  5005.5    0.07       0  5012.1   0.035       0
Bank Sta=4992.4,5005.5
Exp/Cntr=0.3,0.1

Type RM Length L Ch R = 1,73205,443,443,443
BEGIN DESCRIPTION:
Mapping XS c81cde84
END DESCRIPTION:
XS GIS Cut Line= 3
      1663756.01      6941460.86      1664089.37      6941760.36
      1664842.00      6942614.55
#Sta/Elev= 30
  4556.8 1812.06  4624.6 1807.99  4745.0 1795.09  4823.5 1790.53  4844.4 1788.99
  4861.9 1786.77  4887.0 1783.99  4936.3 1776.72  4958.0 1775.39  4964.7 1773.55
  4978.9 1771.56  4992.8 1771.04  4993.3 1770.54  5005.5 1770.54  5006.0 1771.04
  5028.4 1775.46  5056.5 1776.55  5085.0 1776.26  5113.4 1774.98  5141.9 1777.52
  5177.0 1778.79  5262.4 1777.99  5311.7 1778.38  5325.9 1777.60  5340.2 1778.27
  5389.5 1778.44  5439.8 1779.91  5666.5 1783.82  5857.2 1786.47  6143.4 1793.00
#Mann=4,-1,0
  4556.8    0.07       0  4861.9   0.035       0  4992.8   0.035       0
  5006.0   0.035       0
Bank Sta=4992.8,5006
Exp/Cntr=0.3,0.1

Type RM Length L Ch R = 1,72762,454,454,454
BEGIN DESCRIPTION:
Mapping XS 50005043
END DESCRIPTION:
XS GIS Cut Line= 3
      1663399.27      6941640.57      1663753.43      6942036.40
      1664495.62      6942981.72
#Sta/Elev= 30
  4466.6 1810.15  4603.4 1804.85  4624.3 1803.67  4660.2 1800.37  4711.6 1798.17
  4758.9 1794.99  4780.6 1792.28  4825.8 1789.49  4858.3 1787.35  4876.4 1784.45
  4915.1 1779.62  4929.3 1775.82  4950.3 1772.00  4957.8 1771.41  4978.7 1771.44
  4988.8 1770.65  4989.3 1770.15  5001.6 1770.15  5002.1 1770.65  5028.1 1774.81
  5050.6 1775.64  5121.1 1775.33  5185.3 1773.47  5214.2 1774.72  5355.8 1775.53
  5477.3 1778.10  5541.4 1780.57  5634.5 1782.37  6011.4 1787.50  6199.6 1791.16
#Mann=6,-1,0
  4466.6    0.07       0  4711.6   0.035       0  4825.8    0.07       0
  4876.4   0.035       0  4988.8   0.035       0  5002.1   0.035       0
Bank Sta=4988.8,5002.1
Exp/Cntr=0.3,0.1

Type RM Length L Ch R = 1,72308,438,438,438
BEGIN DESCRIPTION:
Mapping XS 7fff571b
END DESCRIPTION:
XS GIS Cut Line= 3
      1663229.84      6941816.75      1663390.44      6942252.98
      1663787.57      6943157.92
#Sta/Elev= 30
  4535.6 1803.14  4650.3 1795.98  4772.2 1785.14  4827.7 1781.58  4877.9 1779.26
  4931.2 1774.20  4944.2 1770.62  4952.5 1769.77  4988.6 1770.30  5016.9 1770.27
  5028.7 1768.40  5040.0 1768.38  5040.5 1767.88  5052.8 1767.88  5053.3 1768.38
  5060.5 1770.77  5063.6 1771.11  5082.4 1773.06  5131.2 1772.72  5145.6 1770.31
  5151.0 1770.23  5213.4 1771.40  5296.7 1774.84  5325.5 1775.36  5343.4 1776.67
  5348.8 1776.15  5372.2 1777.17  5453.7 1778.31  5616.8 1779.58  5988.7 1785.03
#Mann=6,-1,0
  4535.6    0.07       0  4988.6   0.035       0  5040.0   0.035       0
  5053.3   0.035       0  5063.6    0.07       0  5131.2   0.035       0
Bank Sta=5040,5053.3
Exp/Cntr=0.3,0.1

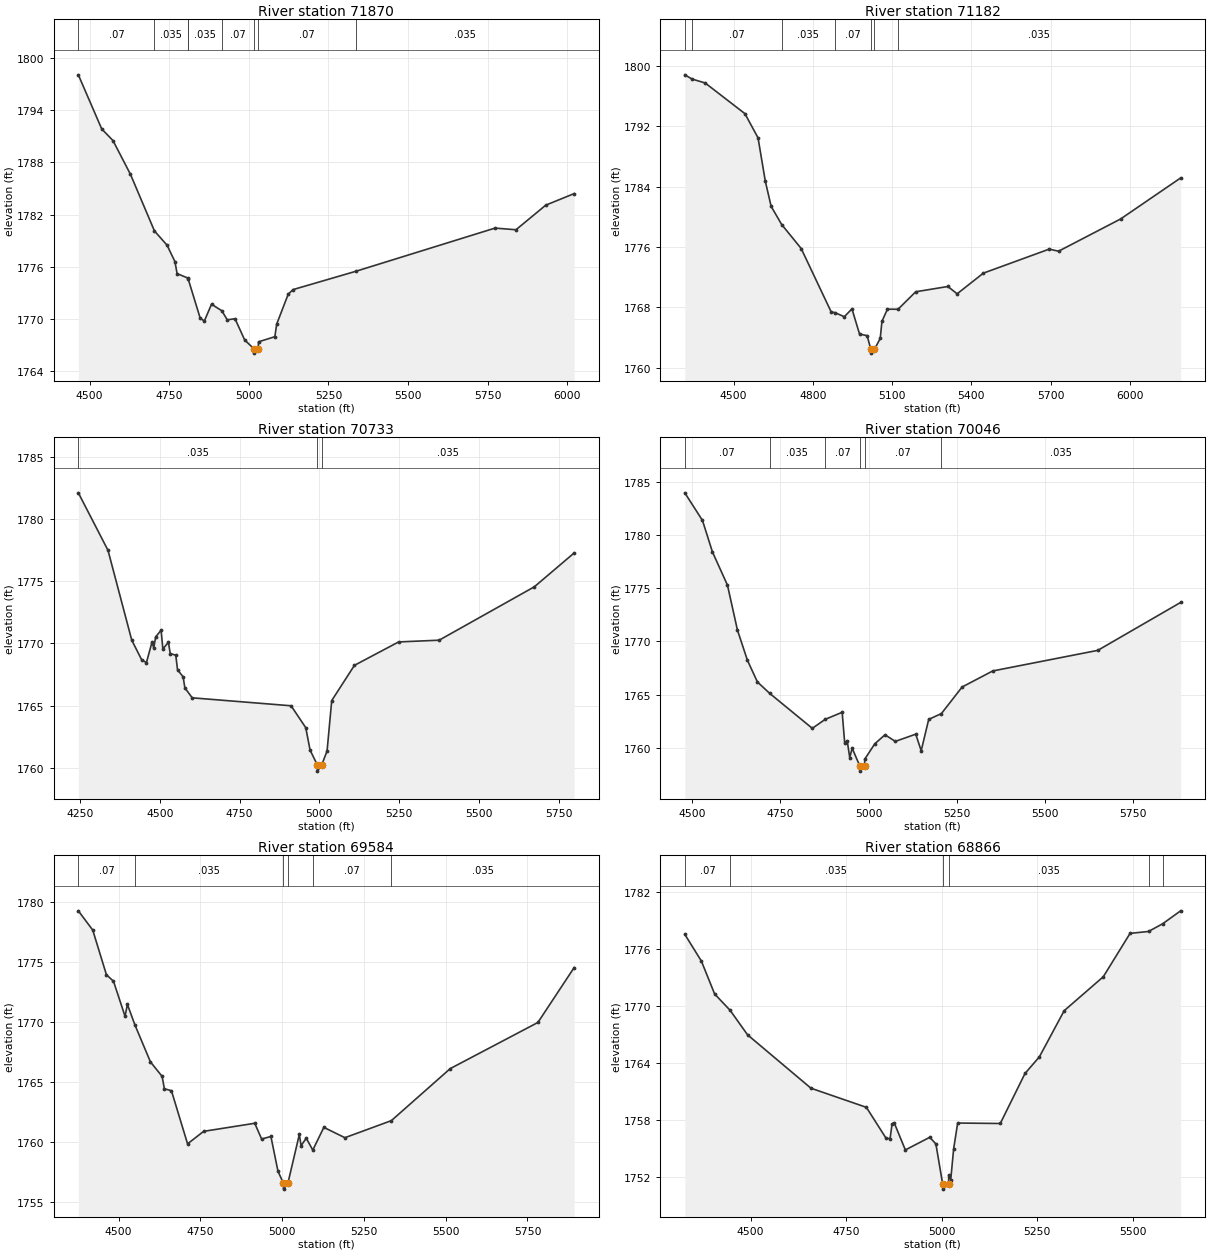
Type RM Length L Ch R = 1,71870,688,688,688
BEGIN DESCRIPTION:
Mapping XS 930f04c6
END DESCRIPTION:
XS GIS Cut Line= 3
      1662852.26      6941988.26      1663045.39      6942493.86
      1663607.44      6943340.20
#Sta/Elev= 30
  4464.7 1798.08  4538.2 1791.85  4573.6 1790.51  4628.4 1786.63  4703.8 1780.11
  4743.4 1778.47  4768.1 1776.58  4774.9 1775.20  4808.1 1774.70  4809.6 1774.60
  4847.6 1770.05  4860.5 1769.75  4883.0 1771.68  4915.5 1770.92  4932.4 1769.88
  4956.8 1770.01  4987.2 1767.56  5016.1 1766.55  5016.6 1766.05  5029.7 1766.55
  5030.6 1767.35  5081.8 1767.94  5087.8 1769.40  5123.8 1772.83  5138.9 1773.36
  5336.4 1775.47  5773.3 1780.44  5839.2 1780.25  5932.7 1783.08  6021.9 1784.41
#Mann=8,-1,0
  4464.7    0.07       0  4703.8   0.035       0  4808.1    0.07       0
  4809.6   0.035       0  4915.5    0.07       0  5016.1    0.07       0
  5029.7    0.07       0  5336.4   0.035       0
Bank Sta=5016.1,5029.7
Exp/Cntr=0.3,0.1

Type RM Length L Ch R = 1,71182,449,449,449
BEGIN DESCRIPTION:
Mapping XS 8f2155d3
END DESCRIPTION:
XS GIS Cut Line= 3
      1662016.73      6942257.31      1662552.76      6942684.84
      1663480.46      6943432.63
#Sta/Elev= 30
  4315.1 1798.83  4342.4 1798.27  4392.2 1797.75  4542.7 1793.68  4592.4 1790.47
  4619.9 1784.72  4642.0 1781.38  4681.9 1778.97  4755.7 1775.79  4869.4 1767.37
  4883.7 1767.28  4919.0 1766.74  4947.9 1767.78  4976.7 1764.44  5005.4 1764.23
  5019.4 1762.41  5019.9 1761.91  5033.1 1762.41  5055.0 1763.86  5061.5 1766.13
  5082.3 1767.74  5122.4 1767.73  5189.4 1770.05  5311.0 1770.75  5346.2 1769.78
  5445.4 1772.52  5694.9 1775.71  5730.1 1775.43  5965.2 1779.71  6192.3 1785.15
#Mann=7,-1,0
  4315.1   0.035       0  4342.4    0.07       0  4681.9   0.035       0
  4883.7    0.07       0  5019.4    0.07       0  5033.1    0.07       0
  5122.4   0.035       0
Bank Sta=5019.4,5033.1
Exp/Cntr=0.3,0.1

Type RM Length L Ch R = 1,70733,687,687,687
BEGIN DESCRIPTION:
Mapping XS 19b286e1
END DESCRIPTION:
XS GIS Cut Line= 3
      1661614.58      6942714.65      1662303.86      6943030.64
      1662989.59      6943435.13
#Sta/Elev= 30
  4244.4 1782.10  4337.4 1777.48  4411.9 1770.26  4442.9 1768.69  4457.9 1768.46
  4475.4 1770.11  4480.9 1769.63  4486.9 1770.53  4503.9 1771.06  4509.4 1769.56
  4526.9 1770.09  4532.4 1769.19  4549.9 1769.05  4555.4 1767.88  4572.9 1767.32
  4578.4 1766.43  4601.4 1765.63  4911.4 1764.99  4957.4 1763.23  4970.9 1761.43
  4993.6 1760.24  4994.1 1759.74  5007.4 1760.24  5024.2 1761.36  5038.8 1765.41
  5110.0 1768.24  5248.5 1770.12  5375.5 1770.26  5674.0 1774.55  5798.8 1777.27
#Mann=3,-1,0
  4244.4   0.035       0  4993.6   0.035       0  5007.4   0.035       0
Bank Sta=4993.6,5007.4
Exp/Cntr=0.3,0.1

Type RM Length L Ch R = 1,70046,462,462,462
BEGIN DESCRIPTION:
Mapping XS d20ed1b7
END DESCRIPTION:
XS GIS Cut Line= 3
      1661343.78      6942908.40      1661708.38      6943285.15
      1662458.41      6943746.98
#Sta/Elev= 30
  4479.0 1783.99  4529.1 1781.39  4557.4 1778.42  4599.9 1775.30  4628.1 1771.08
  4656.4 1768.23  4684.7 1766.19  4719.2 1765.12  4840.3 1761.82  4877.2 1762.67
  4925.0 1763.33  4932.2 1760.42  4939.2 1760.66  4946.4 1759.07  4953.3 1759.95
  4974.7 1758.29  4975.2 1757.79  4988.5 1758.29  4988.8 1758.91  5017.6 1760.37
  5046.3 1761.21  5075.6 1760.59  5133.5 1761.27  5148.9 1759.71  5170.2 1762.66
  5206.2 1763.21  5264.9 1765.71  5351.6 1767.22  5649.4 1769.16  5884.1 1773.67
#Mann=6,-1,0
  4479.0    0.07       0  4719.2   0.035       0  4877.2    0.07       0
  4974.7    0.07       0  4988.5    0.07       0  5206.2   0.035       0
Bank Sta=4974.7,4988.5
Exp/Cntr=0.3,0.1

Type RM Length L Ch R = 1,69584,718,718,718
BEGIN DESCRIPTION:
Mapping XS 446c3d14
END DESCRIPTION:
XS GIS Cut Line= 3
      1660992.41      6943178.85      1661448.11      6943593.31
      1662305.26      6943866.74
#Sta/Elev= 30
  4377.0 1779.26  4421.0 1777.66  4462.9 1773.94  4484.5 1773.40  4519.7 1770.49
  4527.1 1771.47  4549.9 1769.77  4597.4 1766.69  4633.2 1765.48  4640.0 1764.45
  4661.6 1764.29  4710.9 1759.87  4760.2 1760.91  4916.3 1761.58  4937.3 1760.27
  4965.7 1760.48  4987.3 1757.59  5003.7 1756.60  5004.2 1756.10  5017.7 1756.60
  5052.6 1760.65  5057.9 1759.71  5073.7 1760.34  5093.7 1759.35  5127.5 1761.24
  5191.9 1760.38  5333.9 1761.80  5513.9 1766.13  5781.9 1769.97  5892.7 1774.54
#Mann=6,-1,0
  4377.0    0.07       0  4549.9   0.035       0  5003.7   0.035       0
  5017.7   0.035       0  5093.7    0.07       0  5333.9   0.035       0
Bank Sta=5003.7,5017.7
Exp/Cntr=0.3,0.1

Type RM Length L Ch R = 1,68866,620,620,620
BEGIN DESCRIPTION:
Mapping XS 92fb0df1
END DESCRIPTION:
XS GIS Cut Line= 3
      1660799.23      6943289.48      1660975.01      6943942.71
      1661161.31      6944534.09
#Sta/Elev= 30
  4328.1 1777.56  4371.4 1774.75  4406.1 1771.29  4446.6 1769.57  4492.3 1766.99
  4658.0 1761.38  4802.9 1759.37  4854.7 1756.10  4864.9 1756.09  4870.0 1757.60
  4875.4 1757.77  4904.8 1754.89  4968.6 1756.22  4984.7 1755.52  5002.5 1751.27
  5003.0 1750.77  5017.8 1751.27  5018.3 1752.28  5023.5 1751.77  5031.1 1755.01
  5041.6 1757.72  5153.0 1757.67  5217.7 1762.93  5255.3 1764.68  5320.1 1769.53
  5422.4 1773.10  5492.4 1777.66  5540.6 1777.86  5577.6 1778.67  5624.6 1780.03
#Mann=6,-1,0
  4328.1    0.07       0  4446.6   0.035       0  5002.5   0.035       0
  5017.8   0.035       0  5540.6    0.07       0  5577.6   0.035       0
Bank Sta=5002.5,5017.8
Exp/Cntr=0.3,0.1

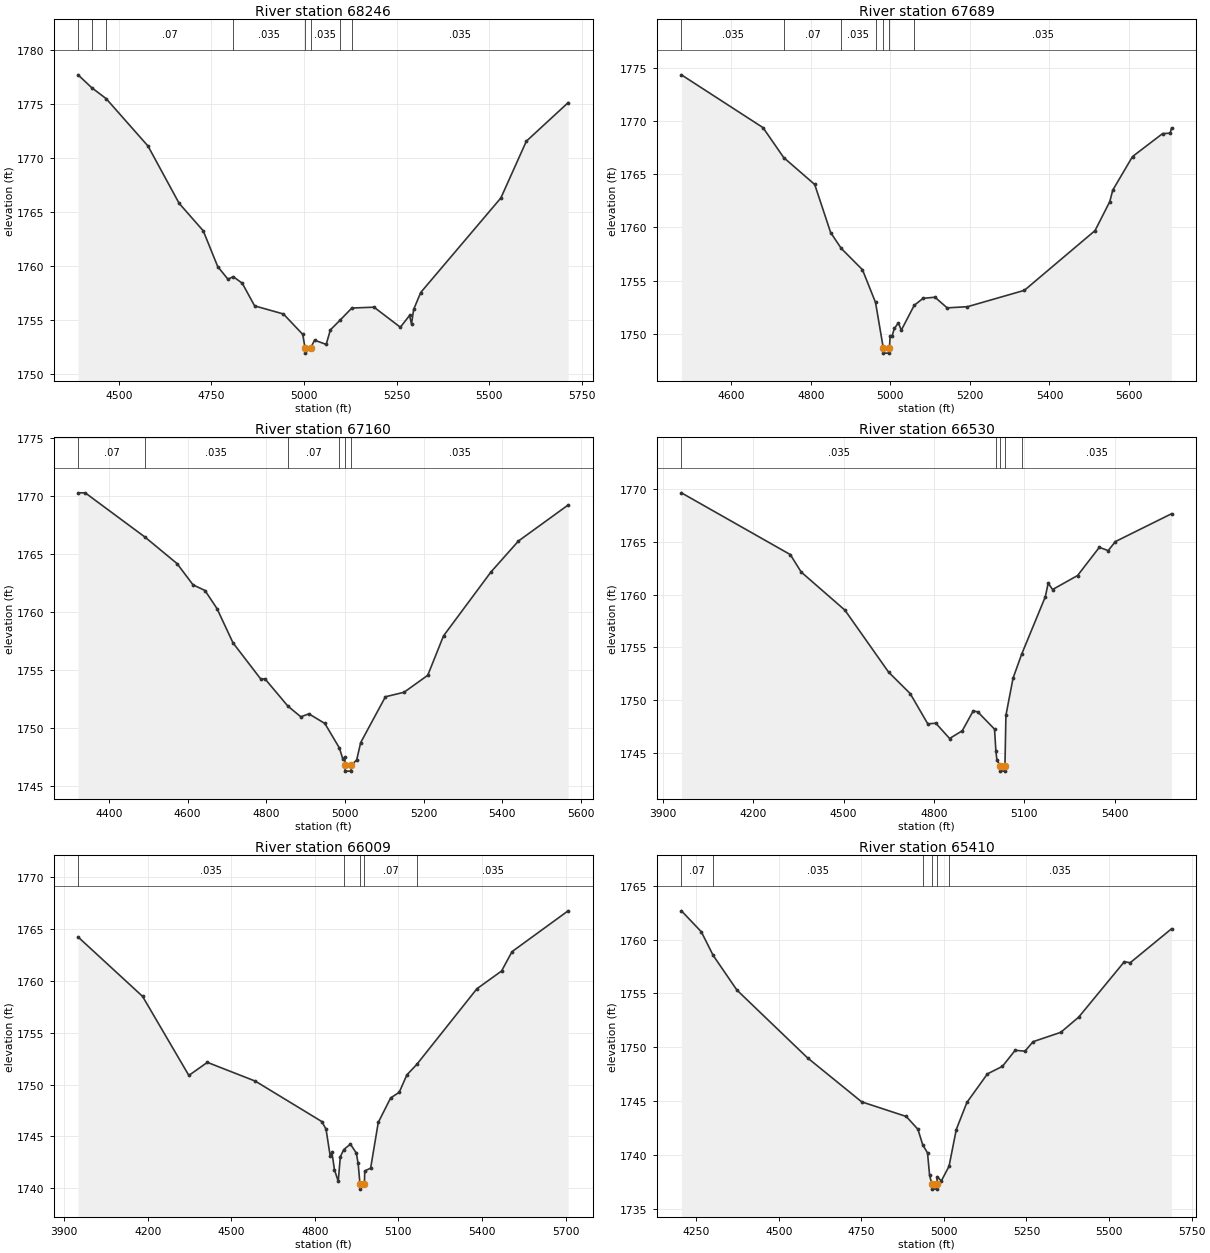
Type RM Length L Ch R = 1,68246,557,557,557
BEGIN DESCRIPTION:
Mapping XS 40852cbb
END DESCRIPTION:
XS GIS Cut Line= 3
      1660235.43      6943306.42      1660409.04      6943896.70
      1660660.38      6944557.53
#Sta/Elev= 30
  4390.1 1777.72  4426.9 1776.53  4466.0 1775.51  4578.8 1771.12  4662.8 1765.81
  4727.9 1763.26  4767.0 1759.94  4794.6 1758.77  4808.8 1759.01  4833.2 1758.40
  4866.5 1756.30  4944.2 1755.55  4996.3 1753.66  5002.5 1752.42  5003.0 1751.92
  5017.8 1752.42  5028.2 1753.12  5059.6 1752.73  5071.0 1754.08  5096.3 1754.95
  5128.8 1756.10  5188.7 1756.18  5259.7 1754.32  5284.5 1755.41  5289.8 1754.62
  5295.6 1755.97  5314.6 1757.54  5531.0 1766.31  5599.7 1771.57  5712.4 1775.14
#Mann=8,-1,0
  4390.1    0.07       0  4426.9   0.035       0  4466.0    0.07       0
  4808.8   0.035       0  5002.5   0.035       0  5017.8   0.035       0
  5096.3    0.07       0  5128.8   0.035       0
Bank Sta=5002.5,5017.8
Exp/Cntr=0.3,0.1

Type RM Length L Ch R = 1,67689,529,529,529
BEGIN DESCRIPTION:
Mapping XS d910f1de
END DESCRIPTION:
XS GIS Cut Line= 3
      1659890.38      6943412.79      1659894.72      6943942.27
      1660040.05      6944629.88
#Sta/Elev= 30
  4474.6 1774.36  4679.8 1769.39  4731.9 1766.57  4809.8 1764.04  4849.8 1759.52
  4876.4 1758.03  4929.8 1756.02  4962.7 1752.94  4982.1 1748.67  4982.6 1748.17
  4997.1 1748.17  4997.6 1748.67  4999.5 1749.75  5004.1 1749.75  5010.0 1750.49
  5020.2 1751.02  5027.5 1750.33  5060.0 1752.67  5082.3 1753.33  5112.2 1753.43
  5142.8 1752.43  5193.9 1752.54  5337.0 1754.08  5514.6 1759.70  5551.7 1762.43
  5559.2 1763.51  5608.9 1766.67  5684.5 1768.83  5703.3 1768.87  5706.9 1769.35
#Mann=7,-1,0
  4474.6   0.035       0  4731.9    0.07       0  4876.4   0.035       0
  4962.7    0.07       0  4982.1    0.07       0  4997.6    0.07       0
  5060.0   0.035       0
Bank Sta=4982.1,4997.6
Exp/Cntr=0.3,0.1

Type RM Length L Ch R = 1,67160,630,630,630
BEGIN DESCRIPTION:
Mapping XS f063fed4
END DESCRIPTION:
XS GIS Cut Line= 3
      1659536.87      6943420.11      1659417.09      6944099.77
      1659372.87      6944653.77
#Sta/Elev= 30
  4321.5 1770.28  4339.7 1770.28  4491.5 1766.47  4573.2 1764.18  4613.8 1762.35
  4644.2 1761.86  4674.8 1760.30  4715.4 1757.35  4786.4 1754.21  4796.6 1754.25
  4855.1 1751.89  4888.0 1750.97  4908.3 1751.23  4948.9 1750.40  4986.0 1748.28
  4994.7 1747.32  4999.8 1747.52  5000.3 1746.79  5000.8 1746.29  5015.5 1746.29
  5016.0 1746.79  5029.9 1747.26  5040.0 1748.75  5102.9 1752.70  5150.3 1753.09
  5210.5 1754.55  5250.6 1757.95  5371.0 1763.45  5441.2 1766.13  5567.4 1769.23
#Mann=6,-1,0
  4321.5    0.07       0  4491.5   0.035       0  4855.1    0.07       0
  4986.0   0.035       0  5000.3   0.035       0  5016.0   0.035       0
Bank Sta=5000.3,5016
Exp/Cntr=0.3,0.1

Type RM Length L Ch R = 1,66530,521,521,521
BEGIN DESCRIPTION:
Mapping XS 81227b20
END DESCRIPTION:
XS GIS Cut Line= 3
      1659417.11      6943120.56      1658851.98      6943993.00
      1658630.64      6944537.23
#Sta/Elev= 30
  3961.7 1769.68  4323.2 1763.81  4359.4 1762.15  4504.5 1758.53  4649.5 1752.64
  4721.2 1750.60  4779.5 1747.73  4806.5 1747.78  4852.0 1746.33  4894.2 1747.07
  4930.5 1748.96  4945.6 1748.86  5001.2 1747.22  5005.8 1745.10  5009.2 1744.28
  5020.0 1743.73  5020.5 1743.23  5035.3 1743.23  5035.8 1743.73  5039.0 1748.53
  5062.7 1752.07  5091.2 1754.34  5169.8 1759.80  5179.3 1761.10  5193.9 1760.49
  5276.9 1761.82  5349.1 1764.50  5378.5 1764.19  5402.6 1765.05  5588.7 1767.69
#Mann=5,-1,0
  3961.7   0.035       0  5005.8    0.07       0  5020.0   0.035       0
  5035.8    0.07       0  5091.2   0.035       0
Bank Sta=5020,5035.8
Exp/Cntr=0.3,0.1

Type RM Length L Ch R = 1,66009,599,599,599
BEGIN DESCRIPTION:
Mapping XS 98dbffce
END DESCRIPTION:
XS GIS Cut Line= 3
      1659003.03      6942834.14      1658427.50      6943722.16
      1658084.06      6944333.59
#Sta/Elev= 30
  3949.9 1764.25  4181.5 1758.52  4347.7 1750.89  4414.2 1752.15  4586.3 1750.34
  4825.0 1746.44  4840.2 1745.71  4855.3 1743.09  4861.3 1743.49  4870.5 1741.78
  4884.0 1740.68  4891.6 1743.05  4904.0 1743.74  4927.8 1744.26  4948.9 1743.40
  4955.5 1742.40  4962.1 1740.42  4962.6 1739.92  4978.0 1740.42  4979.2 1741.67
  5000.4 1741.95  5027.7 1746.35  5072.2 1748.72  5103.0 1749.26  5130.4 1750.94
  5165.9 1751.95  5381.8 1759.25  5470.3 1760.96  5507.9 1762.83  5709.4 1766.77
#Mann=5,-1,0
  3949.9   0.035       0  4904.0    0.07       0  4962.1    0.07       0
  4978.0    0.07       0  5165.9   0.035       0
Bank Sta=4962.1,4978
Exp/Cntr=0.3,0.1

Type RM Length L Ch R = 1,65410,572,572,572
BEGIN DESCRIPTION:
Mapping XS 332c196d
END DESCRIPTION:
XS GIS Cut Line= 3
      1658526.13      6942644.72      1658036.53      6943280.15
      1657787.04      6943914.26
#Sta/Elev= 30
  4205.4 1762.68  4265.5 1760.74  4301.5 1758.54  4373.3 1755.32  4587.1 1749.02
  4751.1 1744.93  4886.1 1743.57  4921.4 1742.38  4935.7 1740.95  4950.4 1740.19
  4956.7 1738.11  4963.3 1737.32  4963.8 1736.82  4978.7 1736.82  4979.2 1737.32
  4979.4 1737.98  4992.2 1737.58  5015.6 1738.95  5037.5 1742.36  5069.7 1744.88
  5131.8 1747.53  5177.2 1748.23  5215.7 1749.72  5245.5 1749.64  5269.9 1750.52
  5353.8 1751.39  5408.0 1752.80  5546.2 1757.95  5564.1 1757.86  5689.0 1761.01
#Mann=6,-1,0
  4205.4    0.07       0  4301.5   0.035       0  4935.7    0.07       0
  4963.3    0.07       0  4979.2    0.07       0  5015.6   0.035       0
Bank Sta=4963.3,4979.2
Exp/Cntr=0.3,0.1