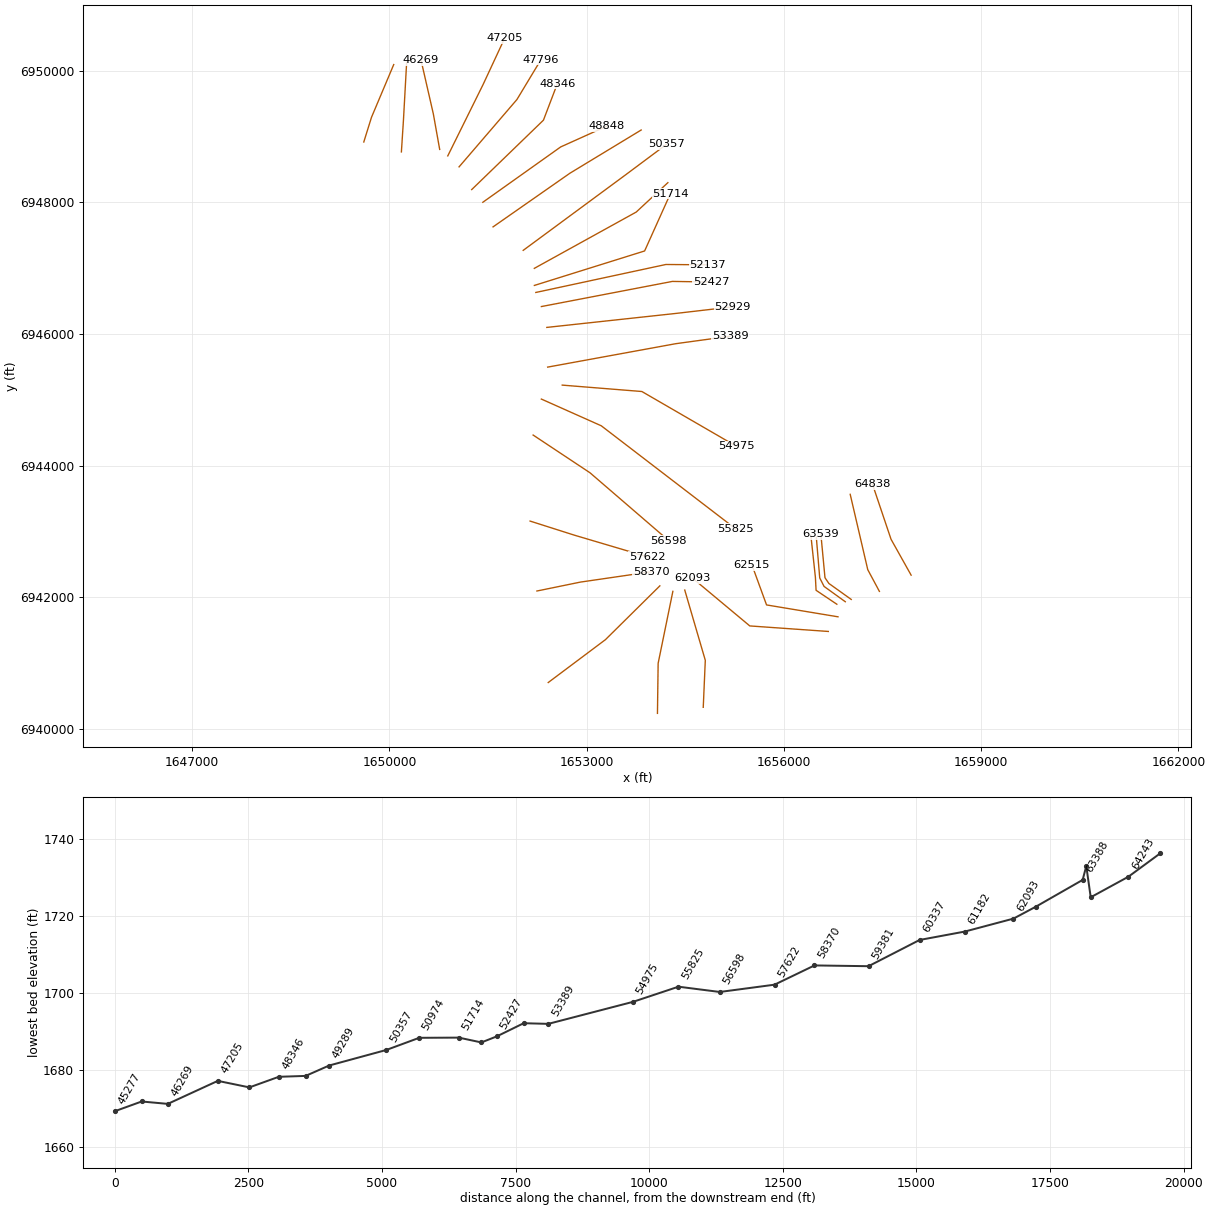
HEC-RAS study Chimney Creek.prj: Chimney Creek Base Level Engineering

--- Chimney Creek.g01 (geometry) --- (continued)

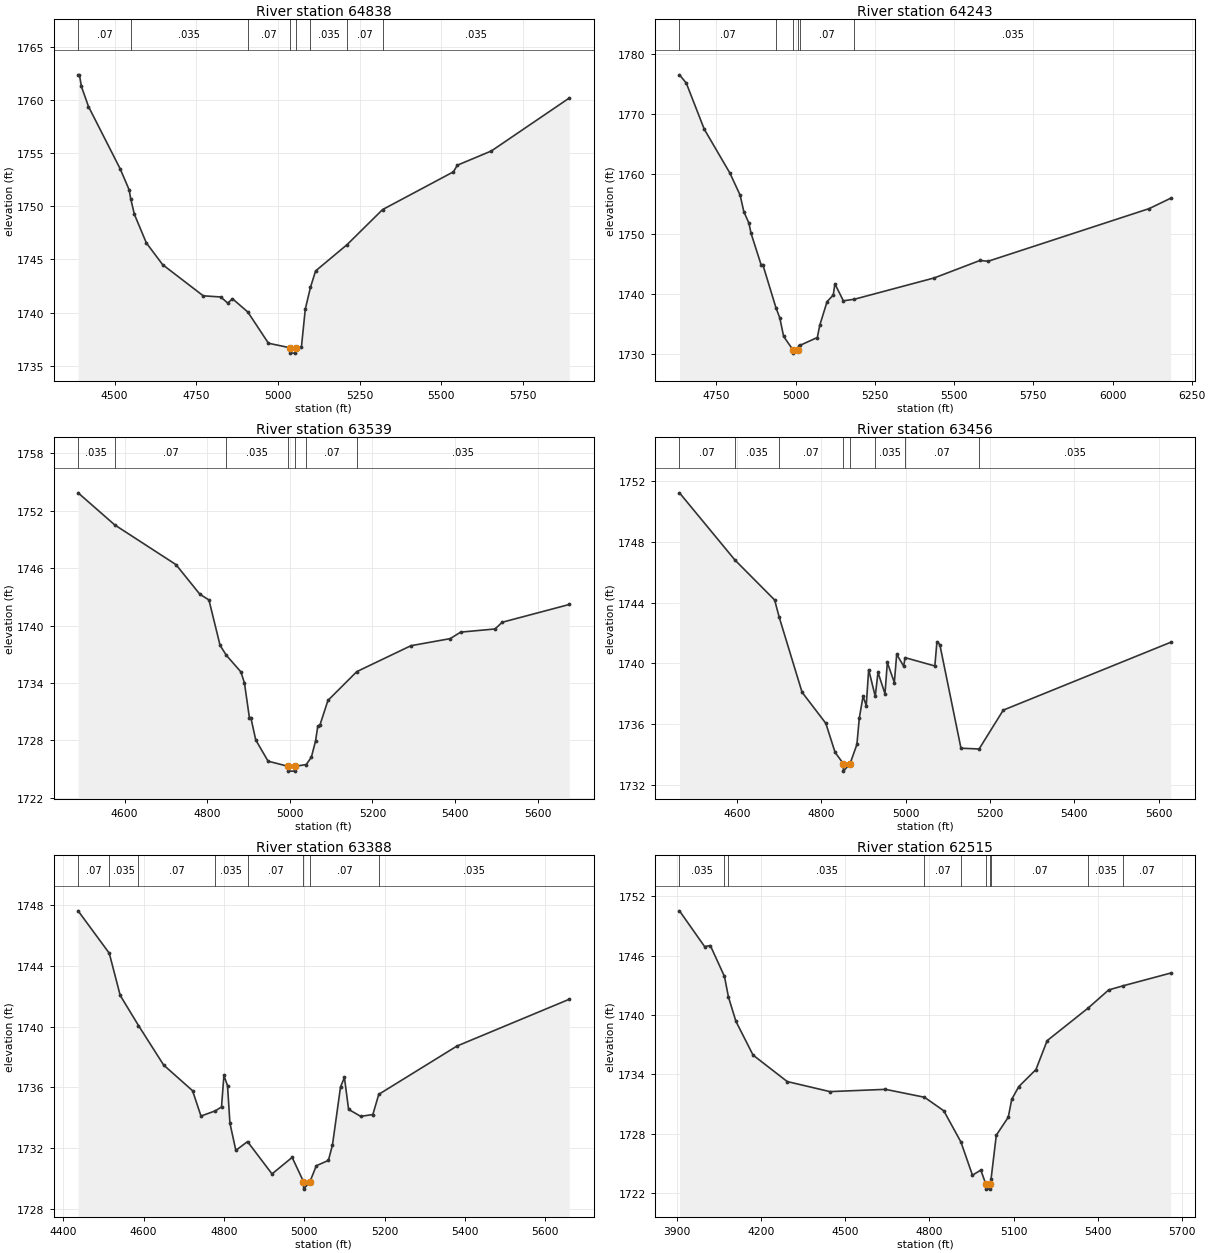
Type RM Length L Ch R = 1,64838,595,595,595
BEGIN DESCRIPTION:
Mapping XS b6cc878c
END DESCRIPTION:
XS GIS Cut Line= 3
      1657935.82      6942335.74      1657630.28      6942880.84
      1657349.03      6943714.17
#Sta/Elev= 30
  4388.0 1762.35  4392.1 1762.35  4398.1 1761.26  4419.8 1759.37  4516.7 1753.52
  4544.2 1751.55  4549.1 1750.70  4560.2 1749.25  4596.9 1746.55  4646.9 1744.50
  4771.3 1741.57  4824.9 1741.46  4846.6 1740.88  4860.6 1741.30  4907.7 1740.05
  4971.0 1737.11  5037.8 1736.68  5038.3 1736.18  5053.5 1736.18  5054.0 1736.68
  5072.1 1736.79  5083.8 1740.32  5099.7 1742.37  5115.4 1743.91  5211.7 1746.38
  5320.6 1749.68  5537.6 1753.23  5549.4 1753.85  5653.7 1755.19  5892.4 1760.17
#Mann=8,-1,0
  4388.0    0.07       0  4549.1   0.035       0  4907.7    0.07       0
  5037.8    0.07       0  5054.0    0.07       0  5099.7   0.035       0
  5211.7    0.07       0  5320.6   0.035       0
Bank Sta=5037.8,5054
Exp/Cntr=0.3,0.1

Type RM Length L Ch R = 1,64243,704,704,704
BEGIN DESCRIPTION:
Mapping XS 91fe931a
END DESCRIPTION:
XS GIS Cut Line= 3
      1657453.21      6942089.15      1657276.11      6942419.04
      1657008.96      6943563.97
#Sta/Elev= 30
  4633.5 1776.60  4654.9 1775.23  4711.6 1767.53  4792.5 1760.20  4825.0 1756.49
  4836.5 1753.75  4852.6 1751.84  4859.2 1750.16  4890.8 1744.92  4896.5 1744.90
  4938.0 1737.69  4950.0 1736.02  4962.2 1732.91  4992.2 1730.62  4992.7 1730.12
  5008.5 1730.62  5010.0 1731.37  5013.5 1731.41  5068.5 1732.73  5076.2 1734.78
  5099.3 1738.72  5118.8 1739.83  5123.9 1741.70  5150.6 1738.86  5185.4 1739.12
  5438.1 1742.69  5581.9 1745.60  5607.2 1745.46  6115.9 1754.26  6183.6 1755.99
#Mann=6,-1,0
  4633.5    0.07       0  4938.0   0.035       0  4992.2   0.035       0
  5008.5   0.035       0  5013.5    0.07       0  5185.4   0.035       0
Bank Sta=4992.2,5008.5
Exp/Cntr=0.3,0.1

Type RM Length L Ch R = 1,63539,83,83,83
BEGIN DESCRIPTION:
Mapping XS 827ee35f
END DESCRIPTION:
XS GIS Cut Line= 4
      1657024.71      6941966.70      1656684.45      6942209.75
      1656625.42      6942296.55      1656562.92      6942959.79
#Sta/Elev= 30
  4487.5 1753.88  4576.1 1750.53  4724.4 1746.38  4782.1 1743.29  4804.3 1742.68
  4831.3 1737.93  4846.6 1736.89  4881.7 1735.16  4890.3 1734.00  4902.2 1730.39
  4905.7 1730.39  4917.6 1728.05  4947.5 1725.83  4996.3 1725.29  4996.8 1724.79
  5012.1 1724.79  5012.6 1725.29  5039.9 1725.48  5052.3 1726.25  5062.3 1727.92
  5067.9 1729.50  5072.9 1729.59  5092.4 1732.18  5162.2 1735.19  5293.3 1737.90
  5388.4 1738.64  5413.8 1739.32  5497.0 1739.65  5514.3 1740.35  5676.8 1742.21
#Mann=7,-1,0
  4487.5   0.035       0  4576.1    0.07       0  4846.6   0.035       0
  4996.3   0.035       0  5012.6   0.035       0  5039.9    0.07       0
  5162.2   0.035       0
Bank Sta=4996.3,5012.6
Exp/Cntr=0.3,0.1

Type RM Length L Ch R = 1,63456,68,68,68
BEGIN DESCRIPTION:
Mapping XS df92543f
END DESCRIPTION:
XS GIS Cut Line= 4
      1656934.44      6941931.97      1656611.53      6942164.61
      1656545.56      6942293.08      1656493.54      6942913.80
#Sta/Elev= 30
  4463.3 1751.24  4594.6 1746.82  4689.0 1744.18  4699.8 1743.05  4754.1 1738.10
  4810.5 1736.05  4832.4 1734.14  4851.8 1733.40  4852.3 1732.90  4868.1 1733.40
  4884.2 1734.66  4889.9 1736.40  4898.8 1737.83  4906.4 1737.22  4912.1 1739.59
  4927.7 1737.83  4934.2 1739.41  4950.8 1738.00  4956.4 1740.06  4973.0 1738.74
  4978.6 1740.60  4995.2 1739.81  4998.4 1740.38  5069.1 1739.83  5074.1 1741.43
  5080.9 1741.24  5131.1 1734.41  5174.1 1734.36  5231.4 1736.92  5628.6 1741.39
#Mann=8,-1,0
  4463.3    0.07       0  4594.6   0.035       0  4699.8    0.07       0
  4851.8    0.07       0  4868.1    0.07       0  4927.7   0.035       0
  4998.4    0.07       0  5174.1   0.035       0
Bank Sta=4851.8,4868.1
Exp/Cntr=0.3,0.1

Type RM Length L Ch R = 1,63388,873,873,873
BEGIN DESCRIPTION:
Mapping XS cbf8eac2
END DESCRIPTION:
XS GIS Cut Line= 4
      1656805.97      6941893.78      1656490.00      6942105.58
      1656479.59      6942303.50      1656410.30      6942944.38
#Sta/Elev= 30
  4436.7 1747.62  4514.3 1744.83  4541.6 1742.05  4587.1 1740.07  4649.7 1737.47
  4721.7 1735.78  4742.7 1734.11  4778.1 1734.45  4793.8 1734.71  4799.8 1736.78
  4808.8 1736.11  4814.8 1733.64  4829.5 1731.85  4858.6 1732.43  4919.6 1730.30
  4969.7 1731.39  4997.9 1729.80  4998.4 1729.30  5014.2 1729.80  5029.9 1730.84
  5060.0 1731.19  5070.1 1732.20  5090.2 1736.03  5099.9 1736.65  5110.3 1734.55
  5140.5 1734.09  5170.7 1734.21  5185.4 1735.54  5380.2 1738.72  5659.9 1741.80
#Mann=8,-1,0
  4436.7    0.07       0  4514.3   0.035       0  4587.1    0.07       0
  4778.1   0.035       0  4858.6    0.07       0  4997.9    0.07       0
  5014.2    0.07       0  5185.4   0.035       0
Bank Sta=4997.9,5014.2
Exp/Cntr=0.3,0.1

Type RM Length L Ch R = 1,62515,422,422,422
BEGIN DESCRIPTION:
Mapping XS 53d7c4e4
END DESCRIPTION:
XS GIS Cut Line= 3
      1656823.32      6941702.81      1655736.53      6941883.36
      1655514.30      6942491.01
#Sta/Elev= 30
  3910.3 1750.54  3999.8 1746.92  4020.1 1747.03  4070.4 1743.90  4084.8 1741.80
  4111.3 1739.35  4172.2 1735.94  4293.8 1733.26  4445.9 1732.24  4643.6 1732.47
  4782.5 1731.67  4851.3 1730.30  4912.4 1727.13  4953.3 1723.78  4983.1 1724.30
  5000.9 1722.87  5001.4 1722.37  5016.9 1722.37  5017.4 1722.87  5019.4 1723.36
  5038.2 1727.83  5080.8 1729.65  5093.0 1731.45  5118.2 1732.75  5179.3 1734.47
  5219.2 1737.40  5365.2 1740.70  5438.1 1742.53  5490.6 1742.96  5659.0 1744.24
#Mann=10,-1,0
  3910.3   0.035       0  4070.4    0.07       0  4084.8   0.035       0
  4782.5    0.07       0  4912.4   0.035       0  5000.9   0.035       0
  5017.4   0.035       0  5019.4    0.07       0  5365.2   0.035       0
  5490.6    0.07       0
Bank Sta=5000.9,5017.4
Exp/Cntr=0.3,0.1

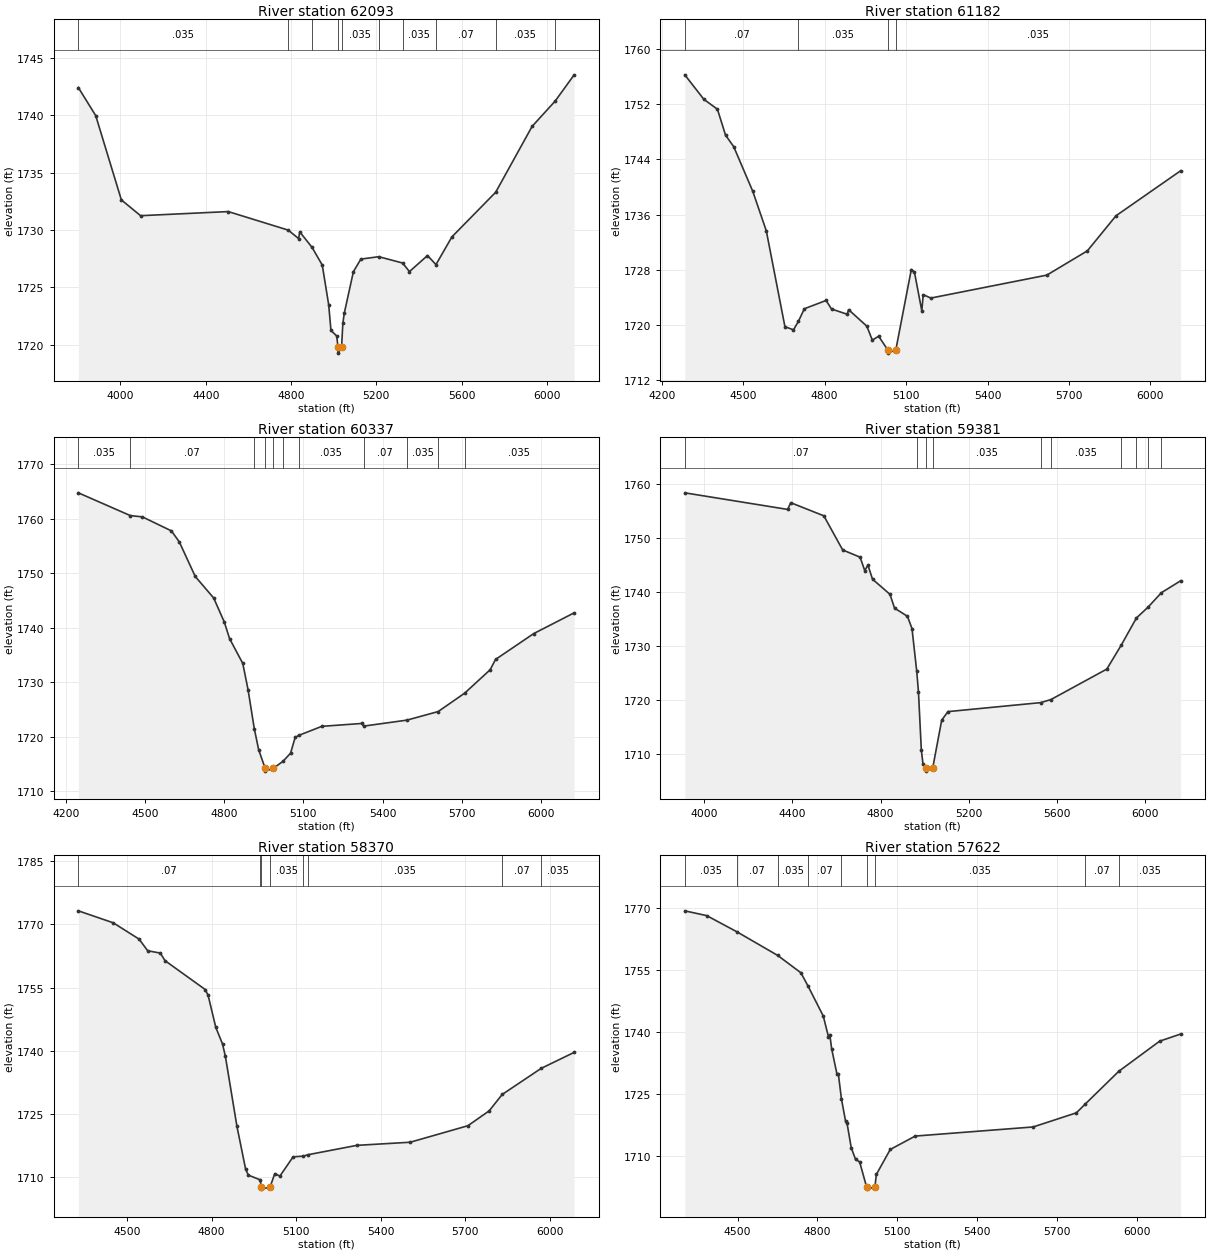
Type RM Length L Ch R = 1,62093,911,911,911
BEGIN DESCRIPTION:
Chimney Creek 96.0
END DESCRIPTION:
XS GIS Cut Line= 3
      1656676.33      6941480.29      1655481.87      6941564.18
      1654615.15      6942286.42
#Sta/Elev= 30
  3802.6 1742.44  3884.1 1739.99  4004.4 1732.63  4094.6 1731.25  4505.7 1731.61
  4787.2 1729.99  4835.9 1729.25  4841.0 1729.84  4899.0 1728.48  4946.7 1726.94
  4976.8 1723.48  4987.5 1721.24  5014.6 1720.74  5020.7 1719.75  5021.2 1719.25
  5037.2 1719.75  5043.3 1721.85  5049.8 1722.72  5092.7 1726.36  5127.9 1727.46
  5211.7 1727.67  5323.3 1727.12  5355.7 1726.37  5440.3 1727.77  5480.1 1726.98
  5554.8 1729.40  5760.2 1733.30  5931.0 1739.05  6038.8 1741.25  6128.2 1743.55
#Mann=10,-1,0
  3802.6   0.035       0  4787.2    0.07       0  4899.0   0.035       0
  5020.7   0.035       0  5037.2   0.035       0  5211.7    0.07       0
  5323.3   0.035       0  5480.1    0.07       0  5760.2   0.035       0
  6038.8    0.07       0
Bank Sta=5020.7,5037.2
Exp/Cntr=0.3,0.1

Type RM Length L Ch R = 1,61182,845,845,845
BEGIN DESCRIPTION:
Mapping XS 01acd33c
END DESCRIPTION:
XS GIS Cut Line= 3
      1654773.71      6940327.96      1654804.96      6941041.47
      1654492.45      6942109.18
#Sta/Elev= 30
  4284.7 1756.27  4354.8 1752.72  4404.9 1751.28  4434.9 1747.51  4464.9 1745.85
  4535.0 1739.38  4585.0 1733.63  4653.6 1719.73  4685.1 1719.27  4703.5 1720.52
  4725.2 1722.33  4805.2 1723.53  4825.3 1722.29  4883.0 1721.53  4888.0 1722.20
  4955.4 1719.80  4975.4 1717.78  4998.9 1718.34  5032.0 1716.39  5032.5 1715.89
  5062.3 1716.39  5119.2 1728.02  5130.7 1727.65  5157.9 1722.03  5163.1 1724.37
  5191.3 1723.88  5618.5 1727.21  5767.8 1730.73  5873.3 1735.82  6111.4 1742.35
#Mann=4,-1,0
  4284.7    0.07       0  4703.5   0.035       0  5032.0   0.035       0
  5062.3   0.035       0
Bank Sta=5032,5062.3
Exp/Cntr=0.3,0.1

Type RM Length L Ch R = 1,60337,956,956,956
BEGIN DESCRIPTION:
Mapping XS 7e1bbd65
END DESCRIPTION:
XS GIS Cut Line= 3
      1654077.09      6940235.51      1654087.51      6940995.90
      1654311.47      6942089.65
#Sta/Elev= 30
  4247.9 1764.73  4444.6 1760.56  4490.4 1760.32  4600.4 1757.75  4630.4 1755.71
  4690.4 1749.40  4760.4 1745.44  4800.4 1741.04  4820.4 1738.01  4870.4 1733.45
  4890.4 1728.64  4913.9 1721.51  4930.5 1717.64  4955.1 1714.21  4955.6 1713.71
  4985.8 1714.21  5023.1 1715.53  5051.3 1717.00  5068.6 1719.88  5083.3 1720.28
  5169.5 1721.92  5320.9 1722.45  5327.8 1721.96  5491.8 1723.06  5610.0 1724.63
  5710.5 1728.01  5806.7 1732.29  5827.1 1734.18  5971.5 1738.92  6124.8 1742.73
#Mann=11,-1,0
  4247.9   0.035       0  4444.6    0.07       0  4913.9   0.035       0
  4955.1   0.035       0  4985.8   0.035       0  5023.1    0.07       0
  5083.3   0.035       0  5327.8    0.07       0  5491.8   0.035       0
  5610.0    0.07       0  5710.5   0.035       0
Bank Sta=4955.1,4985.8
Exp/Cntr=0.3,0.1

Type RM Length L Ch R = 1,59381,1011,1011,1011
BEGIN DESCRIPTION:
Mapping XS 60812d8f
END DESCRIPTION:
XS GIS Cut Line= 3
      1652415.61      6940704.21      1653285.42      6941355.27
      1654113.56      6942172.99
#Sta/Elev= 30
  3911.8 1758.44  4378.2 1755.37  4392.8 1756.61  4542.9 1754.18  4628.3 1747.86
  4707.5 1746.52  4728.3 1744.05  4742.9 1745.04  4763.8 1742.45  4843.0 1739.64
  4863.8 1737.08  4922.2 1735.58  4943.0 1733.29  4964.4 1725.40  4972.2 1721.64
  4985.3 1710.82  4993.0 1708.17  5005.6 1707.40  5006.1 1706.90  5036.6 1707.40
  5077.7 1716.33  5106.0 1717.92  5527.5 1719.59  5573.7 1720.16  5827.2 1725.80
  5893.1 1730.27  5961.5 1735.26  6014.6 1737.28  6074.7 1739.94  6162.1 1742.15
#Mann=10,-1,0
  3911.8    0.07       0  4964.4   0.035       0  5005.6   0.035       0
  5036.6   0.035       0  5527.5    0.07       0  5573.7   0.035       0
  5893.1    0.07       0  5961.5   0.035       0  6014.6    0.07       0
  6074.7   0.035       0
Bank Sta=5005.6,5036.6
Exp/Cntr=0.3,0.1

Type RM Length L Ch R = 1,58370,748,748,748
BEGIN DESCRIPTION:
Mapping XS d74c889d
END DESCRIPTION:
XS GIS Cut Line= 3
      1652243.80      6942094.86      1652905.22      6942230.27
      1653978.17      6942386.53
#Sta/Elev= 30
  4327.0 1773.22  4450.7 1770.38  4542.6 1766.50  4573.2 1763.73  4618.0 1763.18
  4634.4 1761.39  4777.3 1754.52  4787.6 1753.12  4814.7 1745.55  4838.6 1741.59
  4848.8 1738.65  4889.6 1722.09  4920.7 1711.82  4930.5 1710.42  4972.5 1709.30
  4976.1 1707.60  4976.6 1707.10  5007.3 1707.60  5024.1 1710.78  5042.3 1710.20
  5089.1 1714.77  5125.6 1714.94  5140.9 1715.26  5315.2 1717.50  5504.5 1718.24
  5709.3 1722.16  5784.7 1725.69  5831.0 1729.59  5969.4 1735.79  6086.4 1739.59
#Mann=8,-1,0
  4327.0    0.07       0  4972.5   0.035       0  4976.1   0.035       0
  5007.3   0.035       0  5125.6    0.07       0  5140.9   0.035       0
  5831.0    0.07       0  5969.4   0.035       0
Bank Sta=4976.1,5007.3
Exp/Cntr=0.3,0.1

Type RM Length L Ch R = 1,57622,1024,1024,1024
BEGIN DESCRIPTION:
Mapping XS 53ad9166
END DESCRIPTION:
XS GIS Cut Line= 3
      1652139.57      6943157.36      1652811.47      6942943.81
      1653920.45      6942615.80
#Sta/Elev= 30
  4301.8 1769.34  4384.2 1768.18  4497.2 1764.28  4650.5 1758.57  4737.7 1754.37
  4765.0 1751.10  4821.7 1743.92  4840.9 1738.96  4846.2 1739.45  4853.1 1736.02
  4873.2 1729.86  4878.4 1729.89  4889.8 1723.94  4905.4 1718.51  4910.7 1718.11
  4926.6 1712.13  4942.9 1709.26  4958.1 1708.71  4984.4 1702.60  4984.9 1702.10
  5015.6 1702.60  5020.9 1705.64  5073.1 1711.68  5166.9 1714.92  5609.6 1717.12
  5771.8 1720.53  5805.3 1722.66  5931.1 1730.57  6084.6 1737.85  6163.3 1739.57
#Mann=9,-1,0
  4301.8   0.035       0  4497.2    0.07       0  4650.5   0.035       0
  4765.0    0.07       0  4889.8   0.035       0  4984.4   0.035       0
  5015.6   0.035       0  5805.3    0.07       0  5931.1   0.035       0
Bank Sta=4984.4,5015.6
Exp/Cntr=0.3,0.1

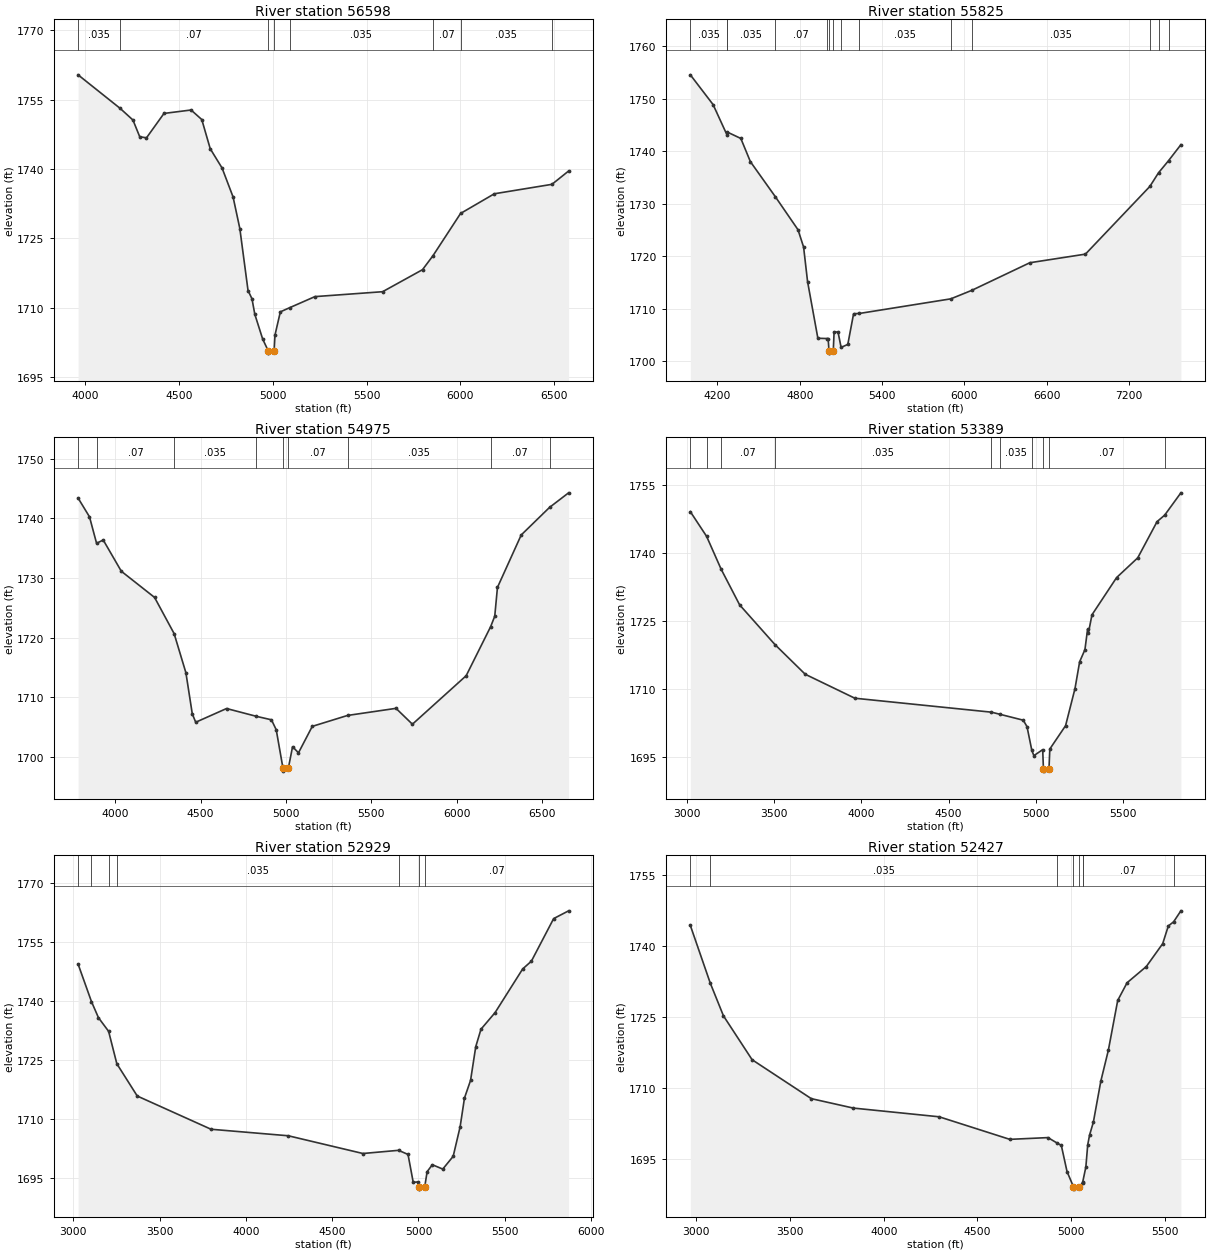
Type RM Length L Ch R = 1,56598,773,773,773
BEGIN DESCRIPTION:
Mapping XS 7b0151b6
END DESCRIPTION:
XS GIS Cut Line= 3
      1652185.92      6944464.65      1653050.51      6943891.73
      1654246.95      6942861.75
#Sta/Elev= 30
  3961.3 1760.34  4186.0 1753.08  4254.0 1750.57  4290.1 1746.96  4326.2 1746.73
  4419.5 1752.00  4563.9 1752.74  4621.0 1750.68  4666.1 1744.37  4729.3 1740.20
  4787.9 1733.95  4823.9 1727.13  4867.7 1713.73  4888.7 1711.96  4903.8 1708.60
  4945.9 1703.23  4975.4 1700.71  4975.9 1700.21  5006.7 1700.71  5011.4 1704.12
  5040.0 1709.13  5090.4 1710.04  5224.3 1712.42  5585.3 1713.48  5798.1 1718.24
  5854.1 1721.27  6001.1 1730.39  6181.1 1734.64  6488.4 1736.68  6577.2 1739.56
#Mann=8,-1,0
  3961.3   0.035       0  4186.0    0.07       0  4975.4    0.07       0
  5006.7    0.07       0  5090.4   0.035       0  5854.1    0.07       0
  6001.1   0.035       0  6488.4    0.07       0
Bank Sta=4975.4,5006.7
Exp/Cntr=0.3,0.1

Type RM Length L Ch R = 1,55825,850,850,850
BEGIN DESCRIPTION:
Mapping XS b900e193
END DESCRIPTION:
XS GIS Cut Line= 3
      1652310.92      6945011.52      1653222.38      6944605.27
      1655269.29      6943037.54
#Sta/Elev= 30
  4002.3 1754.60  4168.1 1748.93  4268.3 1743.22  4271.0 1743.70  4370.3 1742.48
  4440.0 1738.06  4622.7 1731.35  4787.1 1725.09  4827.9 1721.79  4856.8 1715.22
  4932.0 1704.41  4997.8 1704.36  5006.9 1704.32  5013.0 1702.08  5013.5 1701.58
  5044.3 1702.08  5050.4 1705.63  5079.1 1705.59  5101.3 1702.67  5150.2 1703.24
  5192.4 1709.08  5235.1 1709.14  5900.8 1711.92  6052.3 1713.52  6477.2 1718.80
  6882.7 1720.44  7352.3 1733.34  7415.3 1735.93  7488.4 1738.24  7578.5 1741.29
#Mann=14,-1,0
  4002.3   0.035       0  4268.3    0.07       0  4271.0   0.035       0
  4622.7    0.07       0  4997.8   0.035       0  5013.0   0.035       0
  5044.3   0.035       0  5101.3    0.07       0  5235.1   0.035       0
  5900.8    0.07       0  6052.3   0.035       0  7352.3    0.07       0
  7415.3   0.035       0  7488.4    0.07       0
Bank Sta=5013,5044.3
Exp/Cntr=0.3,0.1

Type RM Length L Ch R = 1,54975,1586,1586,1586
BEGIN DESCRIPTION:
Mapping XS b74b19eb
END DESCRIPTION:
XS GIS Cut Line= 3
      1652628.31      6945223.32      1653840.09      6945126.10
      1655274.11      6944296.25
#Sta/Elev= 30
  3782.6 1743.41  3849.5 1740.26  3891.0 1735.82  3929.8 1736.38  4035.9 1731.14
  4230.7 1726.75  4345.1 1720.69  4414.1 1714.13  4451.4 1707.25  4471.5 1705.84
  4652.1 1708.14  4827.0 1706.83  4915.0 1706.25  4943.0 1704.58  4982.4 1698.15
  4982.9 1697.65  5014.0 1698.15  5038.6 1701.74  5073.3 1700.72  5154.1 1705.15
  5360.7 1706.98  5644.3 1708.17  5740.4 1705.51  6055.3 1713.64  6198.8 1721.87
  6222.6 1723.61  6238.4 1728.43  6377.6 1737.22  6543.9 1741.85  6655.1 1744.28
#Mann=9,-1,0
  3782.6   0.035       0  3891.0    0.07       0  4345.1   0.035       0
  4827.0    0.07       0  4982.4    0.07       0  5014.0    0.07       0
  5360.7   0.035       0  6198.8    0.07       0  6543.9   0.035       0
Bank Sta=4982.4,5014
Exp/Cntr=0.3,0.1

Type RM Length L Ch R = 1,53389,460,460,460
BEGIN DESCRIPTION:
Mapping XS 91a0e26f
END DESCRIPTION:
XS GIS Cut Line= 3
      1652406.91      6945496.82      1654355.72      6945852.73
      1655180.20      6945965.55
#Sta/Elev= 30
  3019.1 1749.19  3112.4 1743.74  3195.6 1736.50  3301.8 1728.62  3504.3 1719.86
  3677.9 1713.31  3962.5 1708.02  4746.1 1704.94  4797.2 1704.45  4928.3 1703.17
  4949.8 1701.75  4977.5 1696.50  4989.2 1695.35  5039.8 1696.67  5044.0 1692.43
  5044.5 1691.93  5075.9 1692.43  5080.6 1696.81  5171.0 1701.96  5225.0 1710.15
  5251.7 1716.07  5282.0 1718.74  5297.2 1723.23  5302.2 1722.48  5322.4 1726.43
  5463.7 1734.65  5584.8 1739.00  5695.8 1747.00  5739.2 1748.42  5832.3 1753.35
#Mann=10,-1,0
  3019.1    0.07       0  3112.4   0.035       0  3195.6    0.07       0
  3504.3   0.035       0  4746.1    0.07       0  4797.2   0.035       0
  4977.5    0.07       0  5044.0    0.07       0  5075.9    0.07       0
  5739.2   0.035       0
Bank Sta=5044,5075.9
Exp/Cntr=0.3,0.1

Type RM Length L Ch R = 1,52929,502,502,502
BEGIN DESCRIPTION:
Mapping XS 11413297
END DESCRIPTION:
XS GIS Cut Line= 3
      1652393.95      6946100.13      1654360.06      6946312.79
      1655219.40      6946412.62
#Sta/Elev= 30
  3027.5 1749.47  3105.1 1739.90  3145.7 1735.79  3204.5 1732.32  3252.2 1724.05
  3370.5 1715.83  3798.1 1707.36  4245.6 1705.70  4678.1 1701.18  4884.6 1701.99
  4939.6 1700.94  4969.8 1693.82  5000.0 1693.96  5004.1 1692.60  5004.6 1692.10
  5036.1 1692.60  5050.3 1696.55  5080.5 1698.32  5140.9 1697.21  5201.3 1700.46
  5241.6 1708.00  5266.8 1715.33  5302.0 1719.81  5332.2 1728.43  5362.4 1732.86
  5444.1 1737.09  5604.0 1748.22  5654.4 1750.19  5783.5 1761.05  5870.2 1763.03
#Mann=7,-1,0
  3027.5    0.07       0  3105.1   0.035       0  3204.5    0.07       0
  3252.2   0.035       0  4884.6    0.07       0  5004.1    0.07       0
  5036.1    0.07       0
Bank Sta=5004.1,5036.1
Exp/Cntr=0.3,0.1

Type RM Length L Ch R = 1,52427,290,290,290
BEGIN DESCRIPTION:
Mapping XS 8e0e1fd5
END DESCRIPTION:
XS GIS Cut Line= 3
      1652311.43      6946416.96      1654303.63      6946798.91
      1654891.98      6946790.25
#Sta/Elev= 30
  2968.5 1744.31  3074.8 1732.15  3145.2 1725.24  3298.0 1715.99  3613.6 1707.78
  3837.6 1705.79  4295.8 1703.95  4672.6 1699.19  4876.2 1699.56  4926.4 1698.38
  4947.5 1697.92  4978.0 1692.40  5012.3 1689.19  5012.8 1688.69  5044.4 1689.19
  5060.7 1690.05  5061.3 1690.12  5078.4 1693.35  5088.4 1698.05  5098.4 1700.11
  5118.4 1702.81  5158.4 1711.49  5198.4 1717.98  5248.4 1728.50  5298.4 1732.23
  5401.0 1735.65  5488.4 1740.48  5518.4 1744.21  5546.5 1745.08  5585.4 1747.40
#Mann=8,-1,0
  2968.5    0.07       0  3074.8   0.035       0  4926.4    0.07       0
  5012.3    0.07       0  5044.4    0.07       0  5060.7   0.035       0
  5061.3    0.07       0  5546.5   0.035       0
Bank Sta=5012.3,5044.4
Exp/Cntr=0.3,0.1

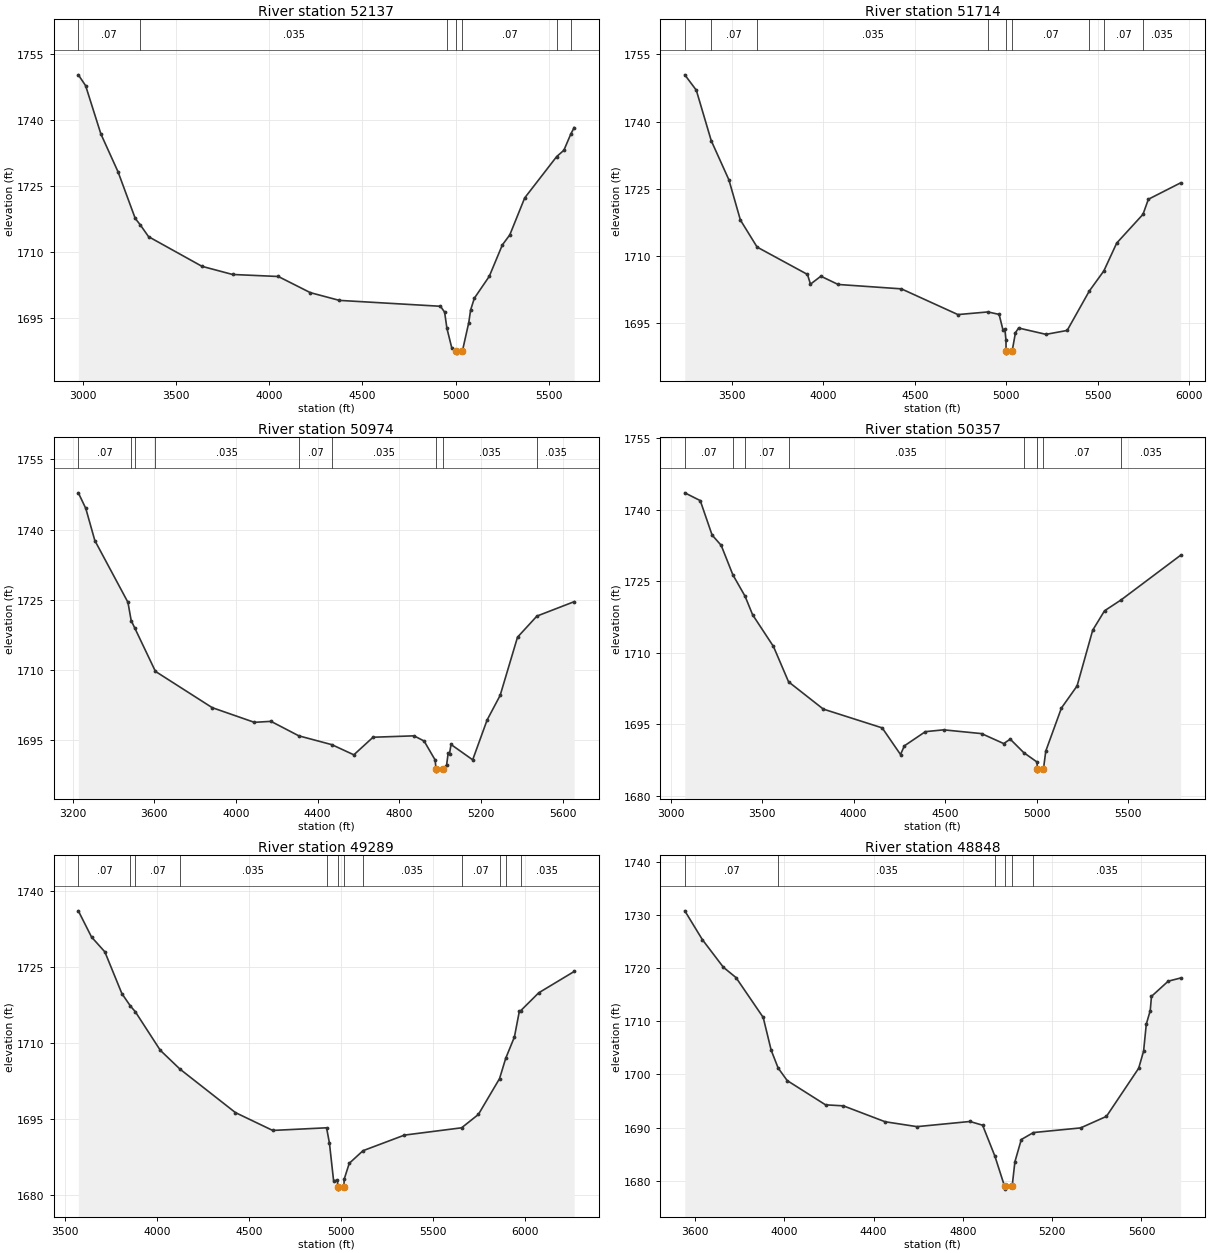
Type RM Length L Ch R = 1,52137,423,423,423
BEGIN DESCRIPTION:
Chimney Creek 80.0
END DESCRIPTION:
XS GIS Cut Line= 3
      1652226.77      6946631.10      1654205.12      6947056.20
      1654840.10      6947051.08
#Sta/Elev= 30
  2976.5 1750.37  3015.6 1747.90  3097.4 1736.93  3189.5 1728.31  3281.5 1717.74
  3308.6 1716.27  3353.1 1713.58  3639.5 1706.84  3803.2 1704.99  4048.7 1704.53
  4220.3 1700.86  4376.0 1699.10  4918.1 1697.76  4940.4 1696.43  4952.7 1692.77
  4979.4 1688.19  5003.8 1687.61  5004.3 1687.11  5035.9 1687.61  5069.9 1694.05
  5079.9 1696.93  5099.9 1699.60  5179.9 1704.57  5249.9 1711.70  5289.9 1713.99
  5369.9 1722.40  5541.5 1731.80  5579.9 1733.22  5616.6 1736.87  5635.0 1738.39
#Mann=7,-1,0
  2976.5    0.07       0  3308.6   0.035       0  4952.7    0.07       0
  5003.8    0.07       0  5035.9    0.07       0  5541.5   0.035       0
  5616.6    0.07       0
Bank Sta=5003.8,5035.9
Exp/Cntr=0.3,0.1

Type RM Length L Ch R = 1,51714,740,740,740
BEGIN DESCRIPTION:
Chimney Creek 79.0
END DESCRIPTION:
XS GIS Cut Line= 3
      1652204.95      6946737.99      1653881.79      6947261.64
      1654273.64      6948131.12
#Sta/Elev= 30
  3243.3 1750.45  3306.2 1747.02  3387.9 1735.75  3484.3 1727.03  3547.2 1718.06
  3638.6 1712.02  3913.8 1705.92  3930.3 1703.75  3987.2 1705.52  4081.4 1703.68
  4427.2 1702.70  4736.2 1696.96  4900.2 1697.55  4961.5 1697.00  4982.4 1693.56
  4992.9 1693.68  4999.1 1691.21  4999.5 1688.86  5000.1 1688.36  5033.0 1688.86
  5050.9 1692.93  5068.0 1693.96  5217.8 1692.55  5333.5 1693.42  5454.1 1702.19
  5534.1 1706.71  5604.4 1712.92  5748.0 1719.33  5777.4 1722.69  5953.7 1726.35
#Mann=9,-1,0
  3243.3   0.035       0  3387.9    0.07       0  3638.6   0.035       0
  4900.2    0.07       0  4999.5    0.07       0  5033.0    0.07       0
  5454.1   0.035       0  5534.1    0.07       0  5748.0   0.035       0
Bank Sta=4999.5,5033
Exp/Cntr=0.3,0.1

Type RM Length L Ch R = 1,50974,617,617,617
BEGIN DESCRIPTION:
Mapping XS 558619d6
END DESCRIPTION:
XS GIS Cut Line= 3
      1652204.22      6946997.48      1653753.69      6947852.51
      1654235.49      6948299.58
#Sta/Elev= 30
  3228.4 1747.85  3264.9 1744.51  3309.2 1737.64  3471.2 1724.43  3487.1 1720.52
  3505.5 1718.85  3605.8 1709.65  3883.7 1701.89  4090.0 1698.75  4171.4 1698.96
  4307.7 1695.86  4469.4 1693.97  4577.0 1691.80  4671.0 1695.56  4871.6 1695.86
  4920.9 1694.75  4974.8 1690.70  4979.3 1688.81  4979.9 1688.31  5012.8 1688.81
  5031.1 1689.63  5038.5 1692.10  5045.3 1692.03  5052.7 1694.01  5158.7 1690.73
  5229.5 1699.27  5293.1 1704.51  5378.1 1716.96  5473.1 1721.48  5655.4 1724.56
#Mann=9,-1,0
  3228.4    0.07       0  3487.1   0.035       0  3505.5    0.07       0
  3605.8   0.035       0  4307.7    0.07       0  4469.4   0.035       0
  4979.3    0.07       0  5012.8   0.035       0  5473.1   0.035       0
Bank Sta=4979.3,5012.8
Exp/Cntr=0.3,0.1

Type RM Length L Ch R = 1,50357,1068,1068,1068
BEGIN DESCRIPTION:
Mapping XS c935e616
END DESCRIPTION:
XS GIS Cut Line= 3
      1652034.90      6947270.88      1653584.42      6948412.40
      1654213.74      6948881.14
#Sta/Elev= 30
  3078.0 1743.52  3162.4 1741.89  3227.1 1734.67  3276.9 1732.50  3340.7 1726.32
  3407.2 1721.84  3448.5 1717.95  3562.5 1711.29  3645.0 1703.88  3834.9 1698.16
  4156.6 1694.22  4256.8 1688.63  4277.7 1690.45  4392.6 1693.43  4492.8 1693.81
  4699.6 1693.02  4820.7 1690.93  4856.2 1691.86  4929.8 1689.04  5002.6 1687.06
  5004.4 1685.65  5005.0 1685.15  5038.0 1685.65  5050.4 1689.35  5135.9 1698.38
  5221.4 1703.01  5306.9 1714.71  5371.5 1718.78  5462.0 1721.06  5787.3 1730.43
#Mann=8,-1,0
  3078.0    0.07       0  3340.7   0.035       0  3407.2    0.07       0
  3645.0   0.035       0  4929.8    0.07       0  5004.4    0.07       0
  5038.0    0.07       0  5462.0   0.035       0
Bank Sta=5004.4,5038
Exp/Cntr=0.3,0.1

Type RM Length L Ch R = 1,49289,441,441,441
BEGIN DESCRIPTION:
Mapping XS 42b8345e
END DESCRIPTION:
XS GIS Cut Line= 3
      1651576.24      6947627.49      1652746.40      6948443.48
      1653829.75      6949099.74
#Sta/Elev= 30
  3573.1 1736.03  3644.7 1730.87  3717.2 1727.93  3809.7 1719.70  3855.4 1717.28
  3882.9 1716.11  4018.2 1708.52  4124.9 1704.81  4426.5 1696.22  4628.9 1692.70
  4921.4 1693.22  4937.0 1690.22  4959.6 1682.79  4980.5 1682.87  4982.4 1681.62
  4983.1 1681.12  5016.1 1681.62  5016.8 1683.04  5044.8 1686.22  5119.3 1688.70
  5344.5 1691.78  5654.9 1693.22  5746.0 1695.85  5861.1 1702.93  5894.7 1706.95
  5941.8 1711.14  5969.0 1716.30  5975.0 1716.29  6073.7 1719.85  6266.3 1724.06
#Mann=12,-1,0
  3573.1    0.07       0  3855.4   0.035       0  3882.9    0.07       0
  4124.9   0.035       0  4921.4    0.07       0  4982.4    0.07       0
  5016.1    0.07       0  5119.3   0.035       0  5654.9    0.07       0
  5861.1   0.035       0  5894.7    0.07       0  5975.0   0.035       0
Bank Sta=4982.4,5016.1
Exp/Cntr=0.3,0.1

Type RM Length L Ch R = 1,48848,502,502,502
BEGIN DESCRIPTION:
Mapping XS ac4eb53b
END DESCRIPTION:
XS GIS Cut Line= 3
      1651420.89      6948001.65      1652605.77      6948842.79
      1653306.28      6949157.88
#Sta/Elev= 30
  3554.3 1730.75  3632.9 1725.34  3727.1 1720.14  3783.7 1718.20  3905.5 1710.71
  3941.2 1704.55  3972.5 1701.19  4013.1 1698.83  4184.8 1694.27  4264.7 1694.08
  4451.7 1691.09  4594.4 1690.17  4831.8 1691.14  4888.4 1690.44  4943.4 1684.63
  4987.0 1678.92  4987.6 1678.42  5020.7 1678.92  5033.1 1683.57  5061.8 1687.75
  5116.2 1689.06  5327.4 1689.93  5443.2 1692.10  5587.6 1701.15  5609.6 1704.36
  5621.7 1709.43  5639.4 1712.00  5644.9 1714.66  5719.8 1717.52  5775.5 1718.12
#Mann=6,-1,0
  3554.3    0.07       0  3972.5   0.035       0  4943.4    0.07       0
  4987.0    0.07       0  5020.7    0.07       0  5116.2   0.035       0
Bank Sta=4987,5020.7
Exp/Cntr=0.3,0.1

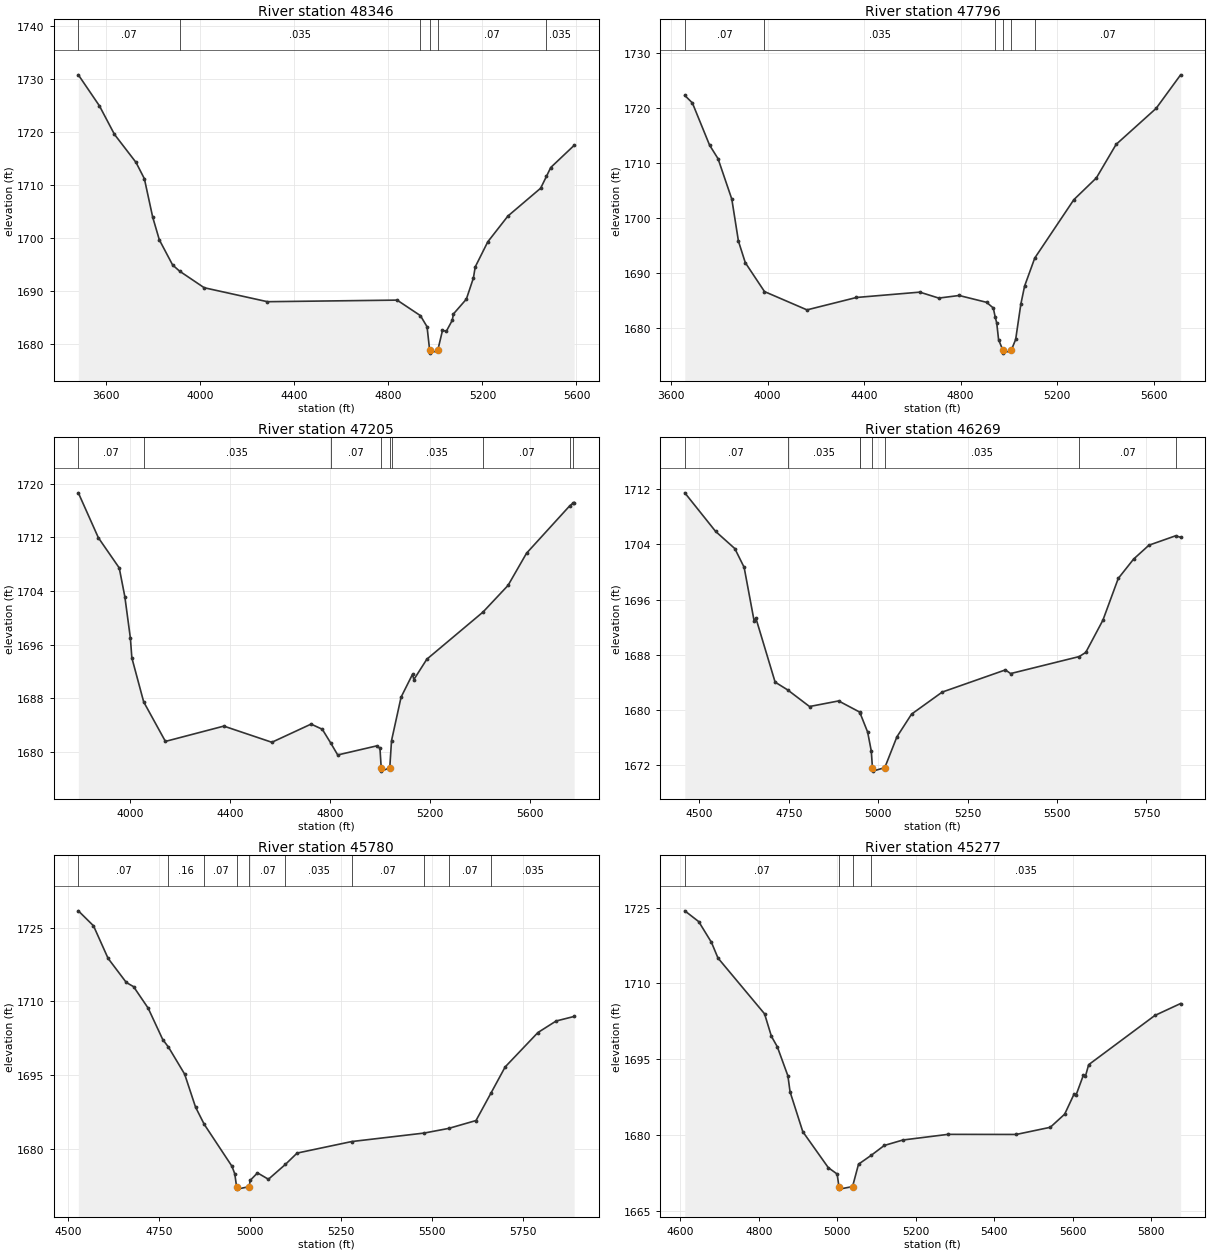
Type RM Length L Ch R = 1,48346,550,550,550
BEGIN DESCRIPTION:
Mapping XS 28e48971
END DESCRIPTION:
XS GIS Cut Line= 3
      1651251.59      6948194.33      1652342.75      6949249.04
      1652553.69      6949801.13
#Sta/Elev= 30
  3481.7 1730.79  3571.5 1724.92  3635.3 1719.54  3727.1 1714.23  3762.6 1711.15
  3797.9 1703.90  3826.2 1699.60  3882.7 1694.85  3912.5 1693.68  4017.0 1690.55
  4285.9 1687.91  4837.4 1688.21  4936.4 1685.28  4964.7 1683.18  4975.9 1678.69
  4976.6 1678.19  5010.1 1678.69  5030.3 1682.47  5047.0 1682.35  5071.7 1684.38
  5077.0 1685.60  5131.8 1688.39  5161.9 1692.40  5169.5 1694.48  5223.0 1699.23
  5308.6 1704.10  5447.8 1709.36  5472.6 1711.61  5490.6 1713.27  5590.3 1717.46
#Mann=6,-1,0
  3481.7    0.07       0  3912.5   0.035       0  4936.4    0.07       0
  4975.9    0.07       0  5010.1    0.07       0  5472.6   0.035       0
Bank Sta=4975.9,5010.1
Exp/Cntr=0.3,0.1

Type RM Length L Ch R = 1,47796,591,591,591
BEGIN DESCRIPTION:
Mapping XS adec6efd
END DESCRIPTION:
XS GIS Cut Line= 3
      1651059.40      6948539.38      1651939.63      6949562.84
      1652304.23      6950167.04
#Sta/Elev= 30
  3656.5 1722.21  3687.9 1720.85  3759.2 1713.19  3794.3 1710.73  3851.4 1703.39
  3878.9 1695.76  3907.3 1691.86  3986.9 1686.61  4163.0 1683.29  4368.2 1685.54
  4630.7 1686.51  4709.4 1685.43  4793.9 1685.90  4907.7 1684.66  4935.5 1683.63
  4943.5 1681.96  4949.8 1680.88  4957.4 1677.88  4975.4 1675.94  4976.1 1675.44
  5009.7 1675.94  5028.2 1677.92  5049.6 1684.31  5065.1 1687.59  5107.4 1692.70
  5269.4 1703.29  5362.8 1707.24  5444.6 1713.32  5610.5 1719.86  5712.1 1725.95
#Mann=6,-1,0
  3656.5    0.07       0  3986.9   0.035       0  4943.5    0.07       0
  4975.4   0.035       0  5009.7    0.07       0  5107.4    0.07       0
Bank Sta=4975.4,5009.7
Exp/Cntr=0.3,0.1

Type RM Length L Ch R = 1,47205,936,936,936
BEGIN DESCRIPTION:
Mapping XS 6c1c2239
END DESCRIPTION:
XS GIS Cut Line= 3
      1650887.53      6948706.03      1651426.61      6949794.61
      1651752.11      6950492.48
#Sta/Elev= 30
  3792.4 1718.61  3872.7 1711.91  3956.1 1707.42  3978.5 1703.15  4000.9 1696.91
  4006.6 1694.02  4054.0 1687.45  4141.0 1681.56  4374.9 1683.84  4567.1 1681.43
  4724.1 1684.14  4769.0 1683.37  4803.7 1681.26  4830.7 1679.54  4987.6 1680.90
  4999.8 1680.53  5004.8 1677.63  5005.5 1677.13  5039.1 1677.63  5046.1 1681.67
  5084.4 1688.16  5130.1 1691.56  5135.6 1690.78  5187.4 1693.81  5412.3 1700.84
  5512.5 1704.81  5586.6 1709.61  5759.1 1716.66  5772.5 1717.07  5777.2 1717.16
#Mann=9,-1,0
  3792.4    0.07       0  4054.0   0.035       0  4803.7    0.07       0
  5004.8    0.07       0  5039.1    0.07       0  5046.1   0.035       0
  5412.3    0.07       0  5759.1   0.035       0  5772.5    0.07       0
Bank Sta=5004.8,5039.1
Exp/Cntr=0.3,0.1

Type RM Length L Ch R = 1,46269,489,489,489
BEGIN DESCRIPTION:
Mapping XS ac1b5382
END DESCRIPTION:
XS GIS Cut Line= 3
      1650764.49      6948804.64      1650668.14      6949343.65
      1650480.64      6950161.38
#Sta/Elev= 30
  4459.0 1711.44  4545.1 1705.86  4598.9 1703.37  4624.9 1700.66  4652.7 1692.94
  4657.8 1693.30  4711.6 1684.04  4746.5 1682.92  4807.8 1680.51  4889.1 1681.32
  4947.9 1679.71  4949.0 1679.58  4970.3 1676.81  4980.5 1674.07  4983.7 1671.66
  4984.4 1671.16  5018.2 1671.66  5052.1 1676.12  5093.1 1679.41  5178.8 1682.60
  5355.5 1685.81  5370.1 1685.28  5561.8 1687.74  5580.2 1688.34  5628.2 1693.01
  5671.1 1699.05  5714.0 1701.85  5756.9 1703.86  5831.5 1705.22  5845.5 1705.00
#Mann=8,-1,0
  4459.0    0.07       0  4746.5   0.035       0  4947.9    0.07       0
  4949.0   0.035       0  4983.7   0.035       0  5018.2   0.035       0
  5561.8    0.07       0  5831.5   0.035       0
Bank Sta=4983.7,5018.2
Exp/Cntr=0.3,0.1

Type RM Length L Ch R = 1,45780,503,503,503
BEGIN DESCRIPTION:
Mapping XS 67df8ddd
END DESCRIPTION:
XS GIS Cut Line= 3
      1650182.03      6948766.36      1650213.28      6949249.04
      1650261.89      6950127.50
#Sta/Elev= 30
  4527.4 1728.46  4569.1 1725.41  4609.2 1718.78  4659.3 1713.87  4679.4 1713.01
  4719.4 1708.64  4759.5 1702.25  4775.3 1700.70  4819.7 1695.21  4849.7 1688.49
  4873.6 1684.98  4949.9 1676.43  4957.6 1674.90  4962.6 1672.28  4963.3 1671.78
  4997.3 1672.28  5000.0 1673.56  5020.1 1675.09  5050.1 1673.79  5096.9 1676.82
  5129.0 1679.12  5279.2 1681.47  5478.5 1683.20  5546.0 1684.15  5621.0 1685.75
  5661.7 1691.28  5701.1 1696.66  5791.2 1703.67  5841.3 1706.02  5890.9 1706.95
#Mann=10,-1,0
  4527.4    0.07       0  4775.3    0.16       0  4873.6    0.07       0
  4962.6    0.07       0  4997.3    0.07       0  5096.9   0.035       0
  5279.2    0.07       0  5478.5   0.035       0  5546.0    0.07       0
  5661.7   0.035       0
Bank Sta=4962.6,4997.3
Exp/Cntr=0.3,0.1

Type RM Length L Ch R = 1,45277,419,419,419
BEGIN DESCRIPTION:
Mapping XS 0d7c9a5a
END DESCRIPTION:
XS GIS Cut Line= 3
      1649609.97      6948917.39      1649727.17      6949292.44
      1650065.39      6950093.75
#Sta/Elev= 30
  4611.7 1724.38  4647.2 1722.24  4679.6 1718.13  4696.2 1715.03  4814.8 1703.98
  4832.3 1699.52  4847.3 1697.45  4874.3 1691.68  4879.8 1688.52  4912.2 1680.63
  4977.2 1673.50  4999.7 1672.24  5004.2 1669.75  5004.9 1669.25  5038.9 1669.75
  5054.1 1674.19  5086.3 1675.94  5119.7 1677.90  5167.1 1678.98  5282.0 1680.10
  5455.7 1680.08  5542.5 1681.50  5579.1 1684.10  5602.8 1688.04  5608.2 1687.90
  5626.5 1691.77  5631.9 1691.59  5640.2 1693.90  5808.8 1703.65  5874.4 1706.02
#Mann=4,-1,0
  4611.7    0.07       0  5004.2    0.07       0  5038.9    0.07       0
  5086.3   0.035       0
Bank Sta=5004.2,5038.9
Exp/Cntr=0.3,0.1