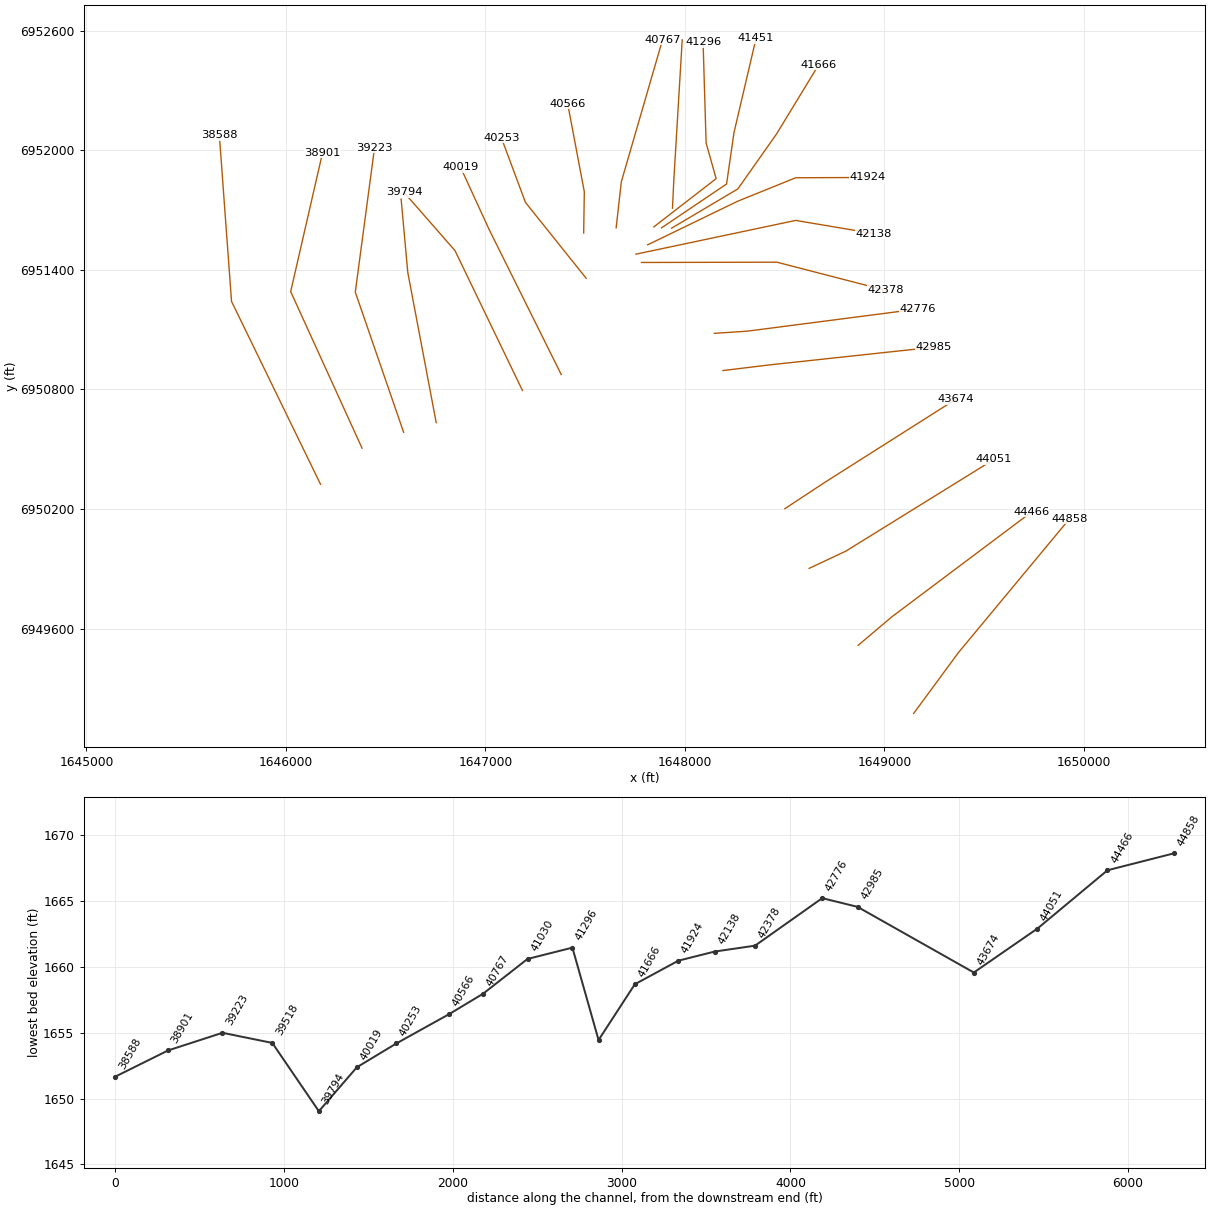
HEC-RAS study Chimney Creek.prj: Chimney Creek Base Level Engineering

--- Chimney Creek.g01 (geometry) --- (continued)

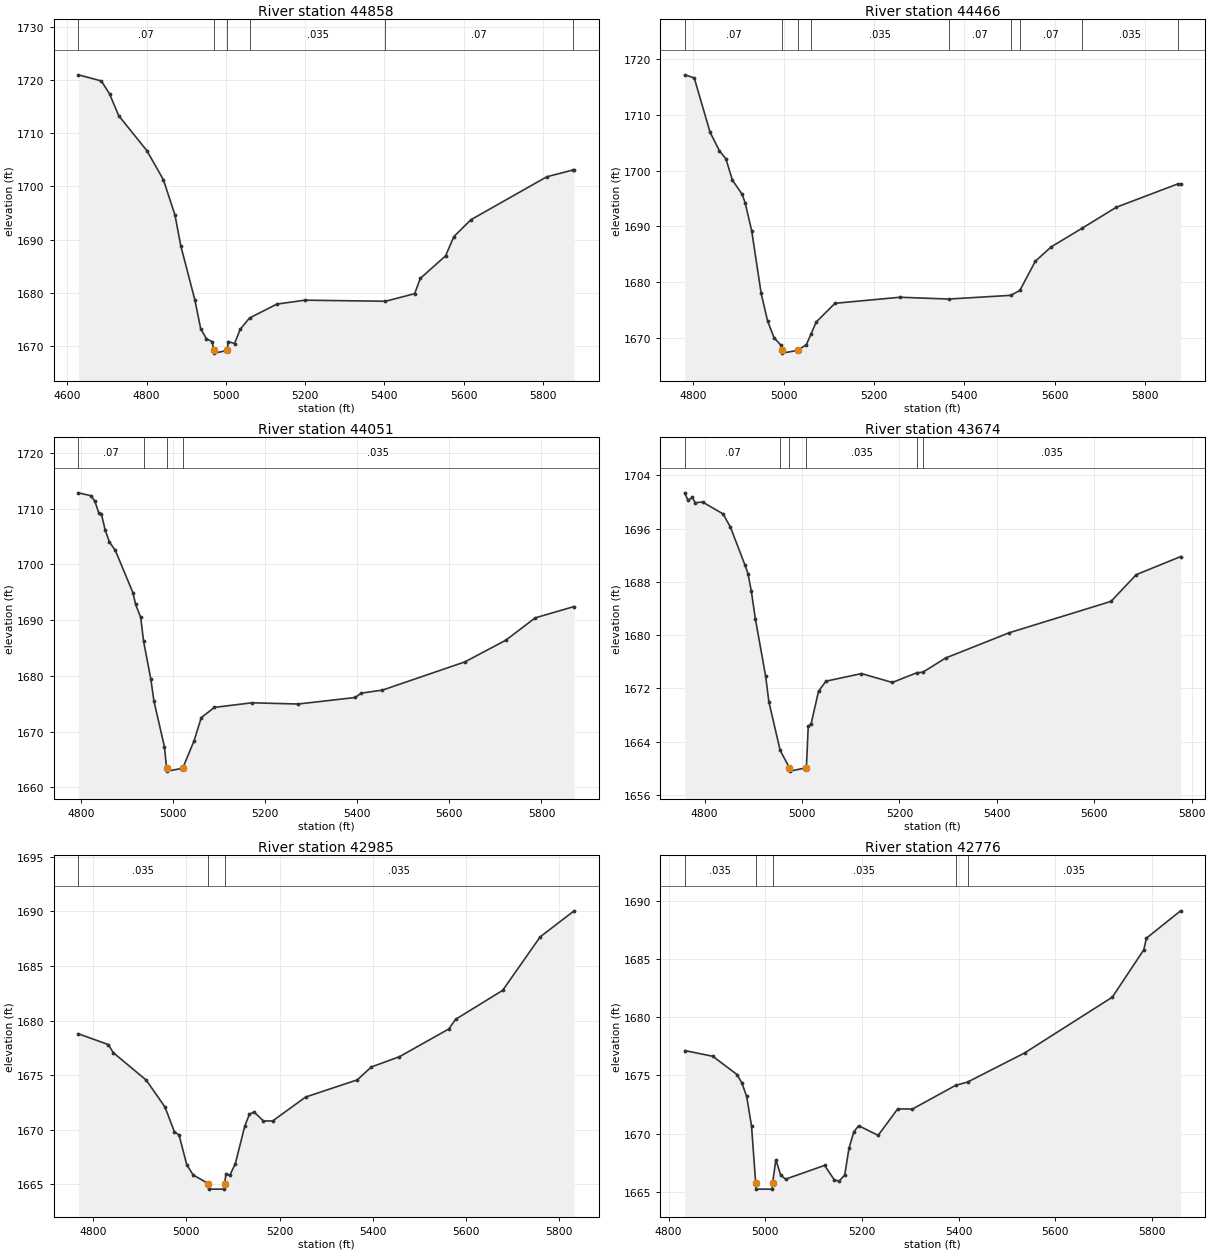
Type RM Length L Ch R = 1,44858,392,392,392
BEGIN DESCRIPTION:
Mapping XS 6c2484ff
END DESCRIPTION:
XS GIS Cut Line= 3
      1649146.43      6949175.24      1649370.40      6949479.94
      1649927.71      6950151.83
#Sta/Elev= 30
  4627.9 1720.98  4685.9 1719.83  4706.7 1717.40  4729.8 1713.30  4800.8 1706.72
  4842.5 1701.26  4871.8 1694.60  4886.5 1688.79  4922.0 1678.63  4936.6 1673.24
  4951.3 1671.31  4965.9 1670.79  4969.4 1669.13  4970.1 1668.63  5004.1 1669.13
  5005.7 1670.81  5022.1 1670.44  5036.4 1673.12  5059.9 1675.24  5128.9 1677.85
  5199.2 1678.59  5403.0 1678.39  5476.5 1679.81  5490.9 1682.69  5554.7 1686.94
  5575.5 1690.55  5618.5 1693.72  5809.9 1701.80  5875.9 1703.08  5879.0 1703.08
#Mann=6,-1,0
  4627.9    0.07       0  4969.4    0.07       0  5004.1    0.07       0
  5059.9   0.035       0  5403.0    0.07       0  5875.9   0.035       0
Bank Sta=4969.4,5004.1
Exp/Cntr=0.3,0.1

Type RM Length L Ch R = 1,44466,415,415,415
BEGIN DESCRIPTION:
Mapping XS 9c828e95
END DESCRIPTION:
XS GIS Cut Line= 3
      1648867.78      6949516.39      1649037.07      6949659.63
      1649737.59      6950185.67
#Sta/Elev= 30
  4781.3 1717.11  4802.2 1716.57  4837.3 1706.85  4858.1 1703.51  4872.4 1702.10
  4886.7 1698.29  4908.6 1695.72  4915.3 1694.14  4929.6 1689.17  4950.4 1678.05
  4964.7 1673.08  4979.0 1670.11  4993.3 1668.84  4996.6 1667.85  4997.3 1667.35
  5031.4 1667.85  5050.5 1668.87  5061.1 1670.81  5072.3 1672.91  5113.9 1676.26
  5257.7 1677.34  5365.3 1677.02  5502.8 1677.68  5523.2 1678.55  5557.6 1683.79
  5593.0 1686.37  5661.9 1689.72  5736.7 1693.43  5872.4 1697.59  5879.1 1697.58
#Mann=9,-1,0
  4781.3    0.07       0  4996.6    0.07       0  5031.4    0.07       0
  5061.1   0.035       0  5365.3    0.07       0  5502.8   0.035       0
  5523.2    0.07       0  5661.9   0.035       0  5872.4    0.07       0
Bank Sta=4996.6,5031.4
Exp/Cntr=0.3,0.1

Type RM Length L Ch R = 1,44051,377,377,377
BEGIN DESCRIPTION:
Mapping XS 8a2b7acc
END DESCRIPTION:
XS GIS Cut Line= 3
      1648622.44      6949902.51      1648806.90      6949989.31
      1649549.10      6950449.39
#Sta/Elev= 30
  4793.8 1712.81  4821.4 1712.29  4829.8 1711.29  4838.6 1709.11  4844.1 1708.96
  4851.9 1706.22  4861.4 1703.98  4874.0 1702.52  4912.5 1694.89  4918.2 1692.82
  4929.3 1690.47  4935.6 1686.18  4951.4 1679.37  4958.1 1675.45  4980.9 1667.28
  4985.6 1663.42  4986.3 1662.92  5020.4 1663.42  5045.5 1668.41  5060.9 1672.52
  5089.6 1674.35  5170.8 1675.17  5271.2 1674.95  5395.5 1676.12  5408.2 1676.90
  5454.3 1677.44  5633.8 1682.51  5722.5 1686.39  5786.2 1690.39  5870.9 1692.43
#Mann=4,-1,0
  4793.8    0.07       0  4935.6   0.035       0  4985.6   0.035       0
  5020.4   0.035       0
Bank Sta=4985.6,5020.4
Exp/Cntr=0.3,0.1

Type RM Length L Ch R = 1,43674,689,689,689
BEGIN DESCRIPTION:
Mapping XS 87e465c2
END DESCRIPTION:
XS GIS Cut Line= 3
      1648500.87      6950201.96      1648704.90      6950336.54
      1649358.08      6950751.01
#Sta/Elev= 30
  4759.3 1701.38  4765.7 1700.26  4774.8 1700.70  4780.8 1699.89  4795.9 1700.00
  4838.0 1698.21  4853.0 1696.24  4883.2 1690.48  4889.2 1689.22  4896.0 1686.58
  4904.2 1682.47  4925.3 1673.87  4932.0 1669.99  4955.2 1662.69  4974.2 1660.08
  4974.9 1659.58  5009.0 1660.08  5012.8 1666.32  5018.7 1666.68  5033.9 1671.57
  5049.2 1673.09  5122.1 1674.23  5185.6 1672.90  5236.3 1674.37  5248.0 1674.43
  5294.9 1676.57  5425.3 1680.36  5634.6 1685.08  5686.3 1689.09  5777.3 1691.80
#Mann=6,-1,0
  4759.3    0.07       0  4955.2   0.035       0  4974.2   0.035       0
  5009.0   0.035       0  5236.3    0.07       0  5248.0   0.035       0
Bank Sta=4974.2,5009
Exp/Cntr=0.3,0.1

Type RM Length L Ch R = 1,42985,209,209,209
BEGIN DESCRIPTION:
Mapping XS eb5a2164
END DESCRIPTION:
XS GIS Cut Line= 3
      1648190.61      6950894.70      1648422.79      6950922.91
      1649247.41      6951011.88
#Sta/Elev= 30
  4768.4 1678.79  4832.7 1677.80  4843.3 1677.06  4913.9 1674.55  4954.2 1672.09
  4974.3 1669.83  4984.4 1669.52  5000.9 1666.81  5014.6 1665.87  5047.4 1665.07
  5048.2 1664.57  5081.6 1664.57  5082.3 1665.07  5085.0 1665.99  5093.2 1665.83
  5105.1 1666.90  5125.2 1670.31  5135.3 1671.43  5145.3 1671.63  5165.4 1670.81
  5185.1 1670.81  5256.0 1673.00  5366.6 1674.57  5396.8 1675.75  5457.1 1676.69
  5562.6 1679.22  5577.8 1680.12  5678.4 1682.76  5758.9 1687.66  5831.7 1690.04
#Mann=3,-1,0
  4768.4   0.035       0  5047.4   0.035       0  5082.3   0.035       0
Bank Sta=5047.4,5082.3
Exp/Cntr=0.3,0.1

Type RM Length L Ch R = 1,42776,398,398,398
BEGIN DESCRIPTION:
Mapping XS 6a6975ba
END DESCRIPTION:
XS GIS Cut Line= 3
      1648147.23      6951081.33      1648312.11      6951092.18
      1649165.02      6951202.86
#Sta/Elev= 30
  4833.5 1677.14  4891.4 1676.65  4941.5 1675.08  4951.5 1674.36  4961.5 1673.20
  4971.6 1670.64  4980.2 1665.73  4981.0 1665.23  5014.4 1665.23  5015.1 1665.73
  5021.8 1667.75  5031.9 1666.43  5042.0 1666.09  5122.7 1667.27  5142.8 1666.02
  5152.9 1665.92  5164.3 1666.46  5173.1 1668.74  5183.2 1670.17  5193.2 1670.68
  5233.4 1669.85  5273.9 1672.13  5304.2 1672.11  5393.6 1674.15  5418.7 1674.44
  5536.1 1676.93  5717.6 1681.73  5782.7 1685.80  5788.2 1686.80  5858.8 1689.15
#Mann=5,-1,0
  4833.5   0.035       0  4980.2   0.035       0  5015.1   0.035       0
  5393.6    0.07       0  5418.7   0.035       0
Bank Sta=4980.2,5015.1
Exp/Cntr=0.3,0.1

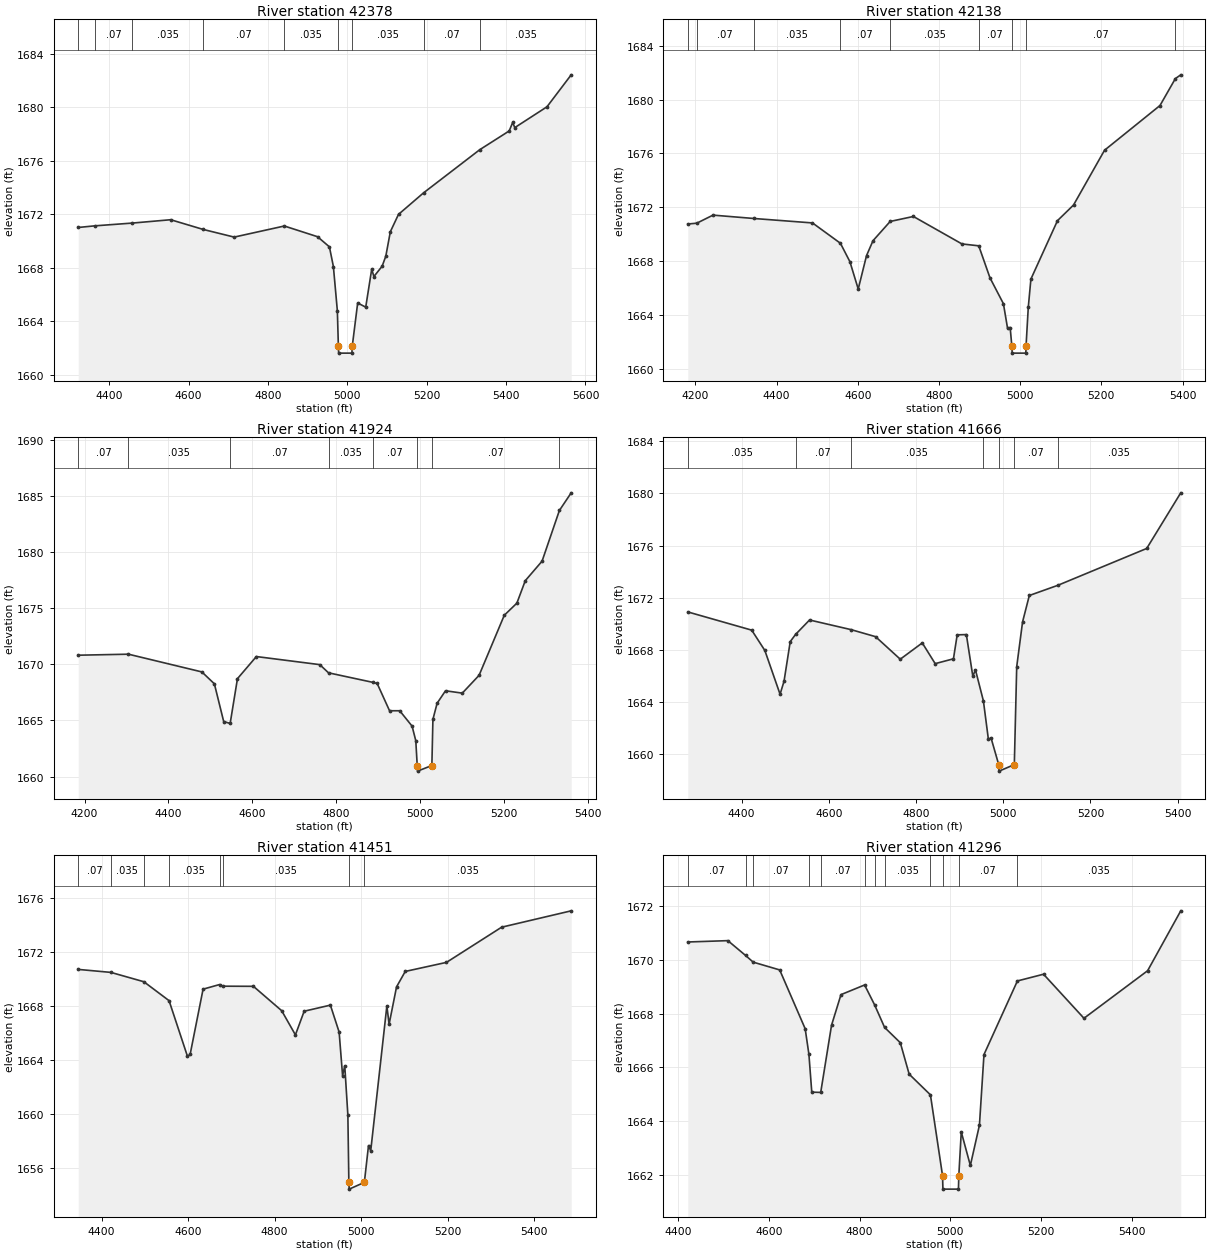
Type RM Length L Ch R = 1,42378,240,240,240
BEGIN DESCRIPTION:
Mapping XS 9311beea
END DESCRIPTION:
XS GIS Cut Line= 3
      1647781.89      6951436.77      1648460.19      6951438.30
      1649006.31      6951297.04
#Sta/Elev= 30
  4321.7 1671.02  4362.8 1671.14  4458.3 1671.35  4554.8 1671.60  4637.1 1670.87
  4714.8 1670.30  4841.2 1671.13  4924.8 1670.33  4954.8 1669.57  4964.8 1668.10
  4974.8 1664.79  4977.4 1662.12  4978.1 1661.62  5011.5 1661.62  5012.3 1662.12
  5026.0 1665.37  5046.3 1665.06  5061.4 1667.90  5066.9 1667.35  5087.6 1668.12
  5096.9 1668.87  5108.3 1670.70  5128.9 1672.00  5192.0 1673.61  5333.7 1676.84
  5407.8 1678.24  5416.7 1678.88  5421.9 1678.49  5503.1 1680.05  5564.1 1682.44
#Mann=9,-1,0
  4321.7   0.035       0  4362.8    0.07       0  4458.3   0.035       0
  4637.1    0.07       0  4841.2   0.035       0  4977.4   0.035       0
  5012.3   0.035       0  5192.0    0.07       0  5333.7   0.035       0
Bank Sta=4977.4,5012.3
Exp/Cntr=0.3,0.1

Type RM Length L Ch R = 1,42138,214,214,214
BEGIN DESCRIPTION:
Mapping XS 2719f398
END DESCRIPTION:
XS GIS Cut Line= 3
      1647754.12      6951478.45      1648554.90      6951647.73
      1648945.49      6951581.77
#Sta/Elev= 30
  4181.1 1670.76  4203.3 1670.82  4243.3 1671.42  4343.9 1671.17  4488.4 1670.84
  4557.2 1669.33  4580.6 1667.96  4601.1 1665.93  4621.5 1668.41  4637.5 1669.52
  4679.8 1670.95  4737.0 1671.32  4856.6 1669.28  4898.0 1669.14  4925.7 1666.76
  4958.8 1664.84  4969.0 1663.01  4975.4 1663.07  4979.6 1661.67  4980.4 1661.17
  5013.8 1661.17  5014.5 1661.67  5020.0 1664.56  5026.5 1666.67  5092.0 1671.01
  5131.5 1672.17  5207.9 1676.24  5344.5 1679.56  5382.4 1681.56  5395.7 1681.84
#Mann=9,-1,0
  4181.1   0.035       0  4203.3    0.07       0  4343.9   0.035       0
  4557.2    0.07       0  4679.8   0.035       0  4898.0    0.07       0
  4979.6    0.07       0  5014.5    0.07       0  5382.4   0.035       0
Bank Sta=4979.6,5014.5
Exp/Cntr=0.3,0.1

Type RM Length L Ch R = 1,41924,258,258,258
BEGIN DESCRIPTION:
Mapping XS 91466358
END DESCRIPTION:
XS GIS Cut Line= 4
      1647813.09      6951525.31      1648263.00      6951743.47
      1648555.06      6951861.72      1648914.36      6951863.09
#Sta/Elev= 30
  4184.9 1670.81  4304.6 1670.90  4479.5 1669.32  4509.3 1668.26  4531.5 1664.90
  4546.9 1664.73  4564.3 1668.72  4609.3 1670.69  4760.4 1669.97  4781.2 1669.24
  4886.9 1668.39  4897.1 1668.29  4926.6 1665.86  4950.8 1665.86  4980.3 1664.49
  4989.1 1663.19  4992.5 1660.98  4993.2 1660.48  5027.4 1660.98  5029.9 1665.09
  5039.9 1666.53  5059.9 1667.64  5099.9 1667.43  5139.9 1669.02  5199.9 1674.37
  5229.9 1675.45  5249.9 1677.45  5289.9 1679.19  5331.2 1683.71  5359.3 1685.28
#Mann=8,-1,0
  4184.9    0.07       0  4304.6   0.035       0  4546.9    0.07       0
  4781.2   0.035       0  4886.9    0.07       0  4992.5    0.07       0
  5027.4    0.07       0  5331.2   0.035       0
Bank Sta=4992.5,5027.4
Exp/Cntr=0.3,0.1

Type RM Length L Ch R = 1,41666,215,215,215
BEGIN DESCRIPTION:
Mapping XS b15d64d6
END DESCRIPTION:
XS GIS Cut Line= 4
      1647932.92      6951608.66      1648264.98      6951805.70
      1648459.08      6952081.53      1648670.82      6952429.35
#Sta/Elev= 30
  4276.6 1670.91  4423.3 1669.51  4453.4 1667.95  4488.3 1664.59  4497.4 1665.59
  4511.6 1668.63  4523.8 1669.18  4555.9 1670.29  4651.1 1669.55  4707.3 1669.01
  4763.9 1667.28  4814.4 1668.53  4844.0 1666.94  4885.9 1667.31  4894.5 1669.15
  4915.5 1669.17  4930.3 1665.98  4936.4 1666.46  4954.6 1664.08  4966.0 1661.14
  4972.1 1661.24  4989.7 1659.19  4990.5 1658.69  5025.5 1659.19  5031.0 1666.71
  5044.4 1670.14  5059.9 1672.17  5125.2 1672.95  5329.1 1675.78  5407.2 1680.05
#Mann=7,-1,0
  4276.6   0.035       0  4523.8    0.07       0  4651.1   0.035       0
  4954.6    0.07       0  4989.7    0.07       0  5025.5    0.07       0
  5125.2   0.035       0
Bank Sta=4989.7,5025.5
Exp/Cntr=0.3,0.1

Type RM Length L Ch R = 1,41451,155,155,155
BEGIN DESCRIPTION:
Mapping XS d21b0926
END DESCRIPTION:
XS GIS Cut Line= 4
      1647882.53      6951610.37      1648208.51      6951830.43
      1648245.72      6952088.46      1648356.32      6952560.99
#Sta/Elev= 30
  4346.0 1670.69  4421.5 1670.47  4497.7 1669.78  4556.0 1668.38  4598.6 1664.26
  4604.7 1664.41  4634.6 1669.23  4672.6 1669.57  4679.9 1669.45  4750.9 1669.44
  4816.2 1667.64  4848.0 1665.85  4868.2 1667.60  4928.8 1668.05  4949.0 1666.06
  4957.0 1662.83  4962.0 1663.57  4969.2 1659.92  4971.5 1654.95  4972.3 1654.45
  5007.3 1654.95  5016.9 1657.67  5022.0 1657.28  5059.3 1667.99  5064.5 1666.64
  5081.7 1669.40  5101.8 1670.54  5197.1 1671.21  5324.5 1673.81  5485.3 1675.02
#Mann=8,-1,0
  4346.0    0.07       0  4421.5   0.035       0  4497.7    0.07       0
  4556.0   0.035       0  4672.6    0.07       0  4679.9   0.035       0
  4971.5   0.035       0  5007.3   0.035       0
Bank Sta=4971.5,5007.3
Exp/Cntr=0.3,0.1

Type RM Length L Ch R = 1,41296,266,266,266
BEGIN DESCRIPTION:
Mapping XS 4098fe7a
END DESCRIPTION:
XS GIS Cut Line= 4
      1647844.39      6951615.62      1648156.14      6951857.19
      1648105.98      6952036.48      1648090.79      6952540.99
#Sta/Elev= 30
  4421.8 1670.67  4510.1 1670.72  4549.0 1670.17  4565.8 1669.92  4624.2 1669.63
  4680.3 1667.44  4688.5 1666.49  4694.8 1665.08  4714.5 1665.07  4738.3 1667.57
  4759.1 1668.71  4811.1 1669.07  4833.1 1668.33  4855.1 1667.49  4889.7 1666.92
  4909.2 1665.75  4956.0 1664.98  4982.7 1661.97  4983.5 1661.47  5017.7 1661.47
  5018.5 1661.97  5023.9 1663.60  5043.9 1662.35  5063.9 1663.85  5073.9 1666.48
  5147.5 1669.22  5205.0 1669.47  5294.0 1667.83  5434.1 1669.60  5507.1 1671.83
#Mann=12,-1,0
  4421.8    0.07       0  4549.0   0.035       0  4565.8    0.07       0
  4688.5   0.035       0  4714.5    0.07       0  4811.1   0.035       0
  4833.1    0.07       0  4855.1   0.035       0  4956.0    0.07       0
  4982.7    0.07       0  5018.5    0.07       0  5147.5   0.035       0
Bank Sta=4982.7,5018.5
Exp/Cntr=0.3,0.1

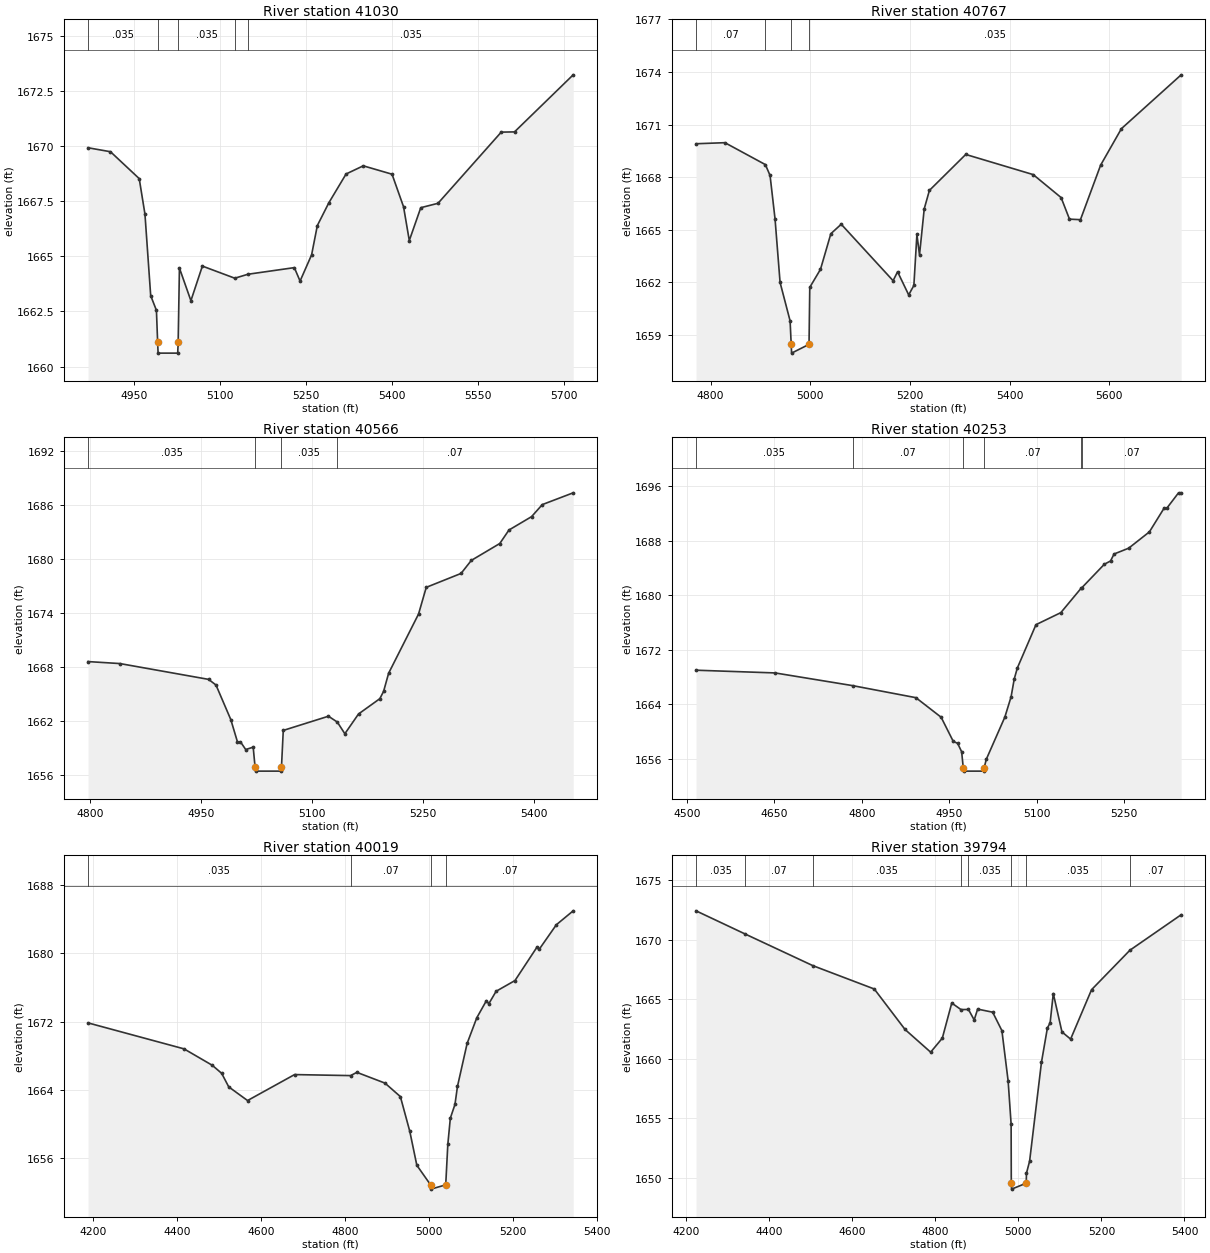
Type RM Length L Ch R = 1,41030,263,263,263
BEGIN DESCRIPTION:
Mapping XS b3b3f1ba
END DESCRIPTION:
XS GIS Cut Line= 3
      1647937.42      6951708.93      1647943.48      6951838.89
      1647986.23      6952553.21
#Sta/Elev= 30
  4869.9 1669.93  4909.0 1669.75  4959.1 1668.53  4969.1 1666.92  4979.1 1663.22
  4989.1 1662.55  4991.2 1661.11  4992.0 1660.61  5026.2 1660.61  5027.0 1661.11
  5029.2 1664.47  5049.2 1662.99  5069.2 1664.56  5125.7 1664.01  5148.7 1664.19
  5229.5 1664.49  5239.5 1663.88  5259.6 1665.07  5269.6 1666.40  5289.6 1667.43
  5319.7 1668.74  5349.7 1669.11  5399.8 1668.73  5419.9 1667.25  5429.9 1665.72
  5449.9 1667.21  5480.0 1667.41  5590.2 1670.64  5613.3 1670.65  5715.6 1673.24
#Mann=5,-1,0
  4869.9   0.035       0  4991.2   0.035       0  5027.0   0.035       0
  5125.7    0.07       0  5148.7   0.035       0
Bank Sta=4991.2,5027
Exp/Cntr=0.3,0.1

Type RM Length L Ch R = 1,40767,201,201,201
BEGIN DESCRIPTION:
Mapping XS 7ca32889
END DESCRIPTION:
XS GIS Cut Line= 3
      1647655.03      6951610.38      1647681.06      6951841.46
      1647887.44      6952553.20
#Sta/Elev= 30
  4770.7 1669.91  4828.7 1669.97  4909.9 1668.72  4919.3 1668.10  4929.3 1665.62
  4939.4 1662.00  4959.5 1659.81  4961.7 1658.47  4962.5 1657.97  4997.5 1658.47
  4999.0 1661.72  5020.5 1662.75  5041.3 1664.78  5062.1 1665.32  5166.2 1662.10
  5175.2 1662.61  5197.5 1661.29  5207.9 1661.83  5214.0 1664.74  5219.2 1663.57
  5228.7 1666.20  5239.1 1667.25  5312.0 1669.30  5447.4 1668.15  5503.4 1666.84
  5520.2 1665.61  5542.2 1665.58  5582.7 1668.69  5624.4 1670.77  5744.3 1673.84
#Mann=4,-1,0
  4770.7    0.07       0  4909.9   0.035       0  4961.7   0.035       0
  4997.5   0.035       0
Bank Sta=4961.7,4997.5
Exp/Cntr=0.3,0.1

Type RM Length L Ch R = 1,40566,313,313,313
BEGIN DESCRIPTION:
Mapping XS 7b04713e
END DESCRIPTION:
XS GIS Cut Line= 3
      1647492.33      6951584.90      1647495.59      6951791.04
      1647412.11      6952233.36
#Sta/Elev= 30
  4797.2 1668.61  4840.3 1668.39  4960.3 1666.63  4970.3 1666.00  4990.3 1662.16
  4999.3 1659.68  5003.4 1659.68  5010.5 1658.82  5020.6 1659.09  5023.1 1656.92
  5023.9 1656.42  5058.1 1656.42  5058.9 1656.92  5061.3 1660.95  5122.4 1662.53
  5134.4 1661.88  5144.6 1660.58  5163.1 1662.78  5191.9 1664.48  5197.0 1665.29
  5203.8 1667.31  5244.3 1673.90  5254.7 1676.87  5301.8 1678.42  5315.7 1679.87
  5354.2 1681.75  5366.6 1683.25  5397.2 1684.74  5411.7 1686.08  5453.5 1687.39
#Mann=4,-1,0
  4797.2   0.035       0  5023.1   0.035       0  5058.9   0.035       0
  5134.4    0.07       0
Bank Sta=5023.1,5058.9
Exp/Cntr=0.3,0.1

Type RM Length L Ch R = 1,40253,234,234,234
BEGIN DESCRIPTION:
Mapping XS 81a2edd4
END DESCRIPTION:
XS GIS Cut Line= 3
      1647504.92      6951357.26      1647200.45      6951738.23
      1647080.02      6952061.54
#Sta/Elev= 30
  4515.5 1669.00  4651.2 1668.60  4784.1 1666.74  4892.9 1664.97  4936.2 1662.10
  4957.0 1658.56  4964.5 1658.27  4971.4 1657.04  4974.2 1654.69  4975.0 1654.19
  5009.3 1654.19  5010.2 1654.69  5013.6 1655.90  5045.6 1662.12  5056.3 1665.10
  5061.7 1667.71  5067.0 1669.32  5099.0 1675.68  5141.7 1677.45  5176.7 1681.05
  5177.8 1681.11  5216.4 1684.55  5227.0 1685.03  5233.0 1686.05  5258.0 1686.90
  5293.7 1689.30  5318.7 1692.75  5324.0 1692.82  5343.7 1695.03  5348.2 1695.03
#Mann=6,-1,0
  4515.5   0.035       0  4784.1    0.07       0  4974.2    0.07       0
  5010.2    0.07       0  5176.7   0.035       0  5177.8    0.07       0
Bank Sta=4974.2,5010.2
Exp/Cntr=0.3,0.1

Type RM Length L Ch R = 1,40019,225,225,225
BEGIN DESCRIPTION:
Mapping XS 7448677c
END DESCRIPTION:
XS GIS Cut Line= 3
      1647379.93      6950874.61      1647018.16      6951602.60
      1646875.42      6951914.02
#Sta/Elev= 30
  4187.9 1671.84  4416.5 1668.80  4483.7 1666.88  4506.1 1665.94  4523.0 1664.35
  4567.8 1662.75  4679.8 1665.79  4813.2 1665.67  4828.2 1666.05  4895.2 1664.79
  4931.8 1663.21  4954.2 1659.15  4971.0 1655.17  5003.8 1652.88  5004.6 1652.38
  5039.8 1652.88  5044.8 1657.62  5050.8 1660.69  5061.8 1662.29  5067.8 1664.41
  5090.8 1669.44  5113.8 1672.44  5136.8 1674.45  5142.3 1674.07  5159.8 1675.54
  5204.8 1676.80  5257.3 1680.72  5262.8 1680.48  5303.3 1683.33  5343.4 1684.96
#Mann=4,-1,0
  4187.9   0.035       0  4813.2    0.07       0  5003.8    0.07       0
  5039.8    0.07       0
Bank Sta=5003.8,5039.8
Exp/Cntr=0.3,0.1

Type RM Length L Ch R = 1,39794,276,276,276
BEGIN DESCRIPTION:
Mapping XS 205e8881
END DESCRIPTION:
XS GIS Cut Line= 3
      1647185.48      6950794.77      1646847.37      6951496.26
      1646591.31      6951789.20
#Sta/Elev= 30
  4224.2 1672.43  4343.2 1670.47  4505.6 1667.82  4653.3 1665.86  4727.3 1662.46
  4789.0 1660.55  4817.1 1661.73  4839.8 1664.68  4862.0 1664.13  4880.0 1664.14
  4893.8 1663.26  4902.1 1664.17  4938.3 1663.91  4960.5 1662.36  4975.5 1658.13
  4982.7 1654.50  4983.1 1649.54  4983.9 1649.04  5019.1 1649.54  5019.6 1650.37
  5027.2 1651.39  5055.7 1659.69  5070.0 1662.58  5076.6 1663.02  5084.2 1665.48
  5105.1 1662.25  5125.9 1661.65  5176.3 1665.80  5268.7 1669.12  5392.0 1672.10
#Mann=8,-1,0
  4224.2   0.035       0  4343.2    0.07       0  4505.6   0.035       0
  4862.0    0.07       0  4880.0   0.035       0  4983.1   0.035       0
  5019.1   0.035       0  5268.7    0.07       0
Bank Sta=4983.1,5019.1
Exp/Cntr=0.3,0.1

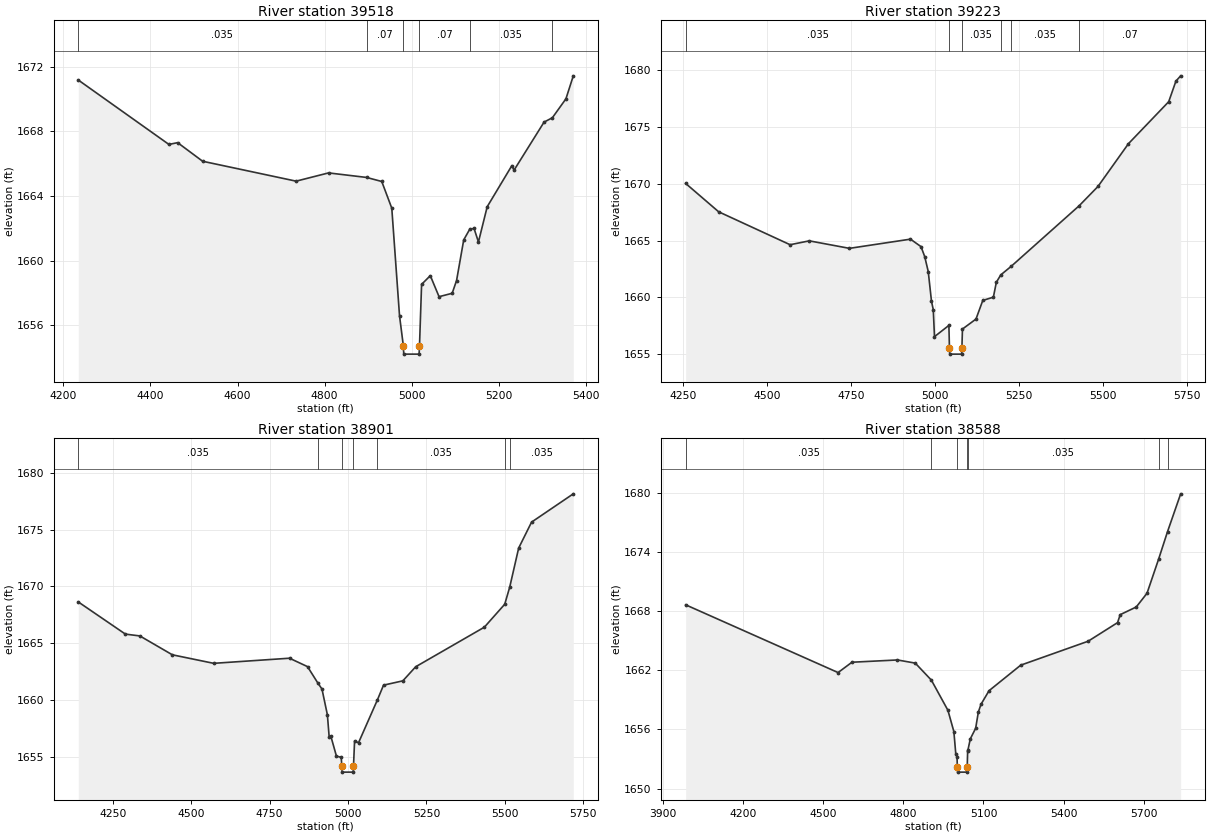
Type RM Length L Ch R = 1,39518,295,295,295
BEGIN DESCRIPTION:
Mapping XS 8f1e522a
END DESCRIPTION:
XS GIS Cut Line= 3
      1646753.21      6950633.58      1646610.82      6951386.67
      1646577.35      6951754.82
#Sta/Elev= 30
  4234.6 1671.17  4442.6 1667.19  4462.6 1667.30  4520.0 1666.15  4734.5 1664.92
  4809.0 1665.43  4896.2 1665.15  4931.1 1664.90  4954.1 1663.25  4971.9 1656.59
  4980.7 1654.73  4981.6 1654.23  5016.8 1654.23  5017.7 1654.73  5022.5 1658.54
  5042.5 1659.08  5062.6 1657.78  5092.7 1657.99  5102.8 1658.78  5119.2 1661.29
  5132.8 1661.94  5142.9 1662.00  5153.0 1661.16  5173.1 1663.34  5229.7 1665.88
  5234.7 1665.60  5303.6 1668.57  5322.7 1668.84  5353.8 1670.01  5370.7 1671.43
#Mann=6,-1,0
  4234.6   0.035       0  4896.2    0.07       0  4980.7    0.07       0
  5017.7    0.07       0  5132.8   0.035       0  5322.7    0.07       0
Bank Sta=4980.7,5017.7
Exp/Cntr=0.3,0.1

Type RM Length L Ch R = 1,39223,322,322,322
BEGIN DESCRIPTION:
Mapping XS 66a289b9
END DESCRIPTION:
XS GIS Cut Line= 3
      1646590.01      6950585.02      1646347.67      6951288.06
      1646444.18      6952012.13
#Sta/Elev= 30
  4256.8 1670.04  4355.1 1667.54  4567.8 1664.64  4625.0 1664.98  4744.5 1664.32
  4926.3 1665.13  4957.7 1664.47  4968.6 1663.60  4979.2 1662.28  4988.9 1659.65
  4994.2 1658.92  4997.8 1656.54  5040.7 1657.53  5042.4 1655.50  5043.3 1655.00
  5078.5 1655.00  5079.4 1655.50  5081.1 1657.21  5121.4 1658.09  5141.6 1659.73
  5173.2 1660.02  5182.0 1661.33  5195.2 1661.98  5226.4 1662.74  5428.2 1668.06
  5484.6 1669.77  5575.4 1673.54  5695.3 1677.24  5716.7 1679.05  5730.9 1679.52
#Mann=6,-1,0
  4256.8   0.035       0  5042.4   0.035       0  5079.4   0.035       0
  5195.2    0.07       0  5226.4   0.035       0  5428.2    0.07       0
Bank Sta=5042.4,5079.4
Exp/Cntr=0.3,0.1

Type RM Length L Ch R = 1,38901,313,313,313
BEGIN DESCRIPTION:
Mapping XS c4f8b14b
END DESCRIPTION:
XS GIS Cut Line= 3
      1646381.69      6950505.11      1646023.89      6951290.66
      1646183.76      6951987.77
#Sta/Elev= 30
  4139.8 1668.63  4290.0 1665.80  4336.1 1665.64  4439.7 1663.98  4571.5 1663.23
  4813.3 1663.68  4870.7 1662.94  4904.5 1661.46  4916.8 1660.97  4934.1 1658.70
  4939.8 1656.73  4945.3 1656.80  4962.9 1655.07  4978.1 1654.96  4980.3 1654.16
  4981.2 1653.66  5016.4 1653.66  5017.3 1654.16  5020.8 1656.41  5033.3 1656.24
  5093.5 1660.01  5113.1 1661.31  5174.7 1661.69  5215.7 1662.93  5434.6 1666.41
  5499.6 1668.43  5515.5 1669.94  5544.0 1673.37  5585.1 1675.65  5718.2 1678.14
#Mann=7,-1,0
  4139.8   0.035       0  4904.5    0.07       0  4980.3    0.07       0
  5017.3    0.07       0  5093.5   0.035       0  5499.6    0.07       0
  5515.5   0.035       0
Bank Sta=4980.3,5017.3
Exp/Cntr=0.3,0.1

Type RM Length L Ch R = 1,38588,282,282,282
BEGIN DESCRIPTION:
Mapping XS 4bc73e97
END DESCRIPTION:
XS GIS Cut Line= 3
      1646173.33      6950324.62      1645727.45      6951241.40
      1645666.46      6952073.81
#Sta/Elev= 30
  3984.5 1668.66  4555.4 1661.78  4607.4 1662.83  4777.8 1663.06  4844.5 1662.74
  4904.9 1661.01  4966.8 1657.95  4989.1 1655.79  4996.4 1653.49  5001.0 1653.20
  5002.1 1652.17  5003.0 1651.67  5038.2 1651.67  5039.1 1652.17  5040.7 1653.77
  5041.9 1653.92  5050.7 1655.05  5070.7 1656.12  5080.8 1657.77  5090.8 1658.56
  5120.9 1659.94  5239.4 1662.53  5491.9 1664.96  5602.2 1666.85  5612.2 1667.66
  5672.3 1668.44  5712.5 1669.83  5756.4 1673.33  5789.4 1676.09  5838.6 1679.93
#Mann=7,-1,0
  3984.5   0.035       0  4904.9    0.07       0  5002.1    0.07       0
  5039.1    0.07       0  5041.9   0.035       0  5756.4    0.07       0
  5789.4   0.035       0
Bank Sta=5002.1,5039.1
Exp/Cntr=0.3,0.1