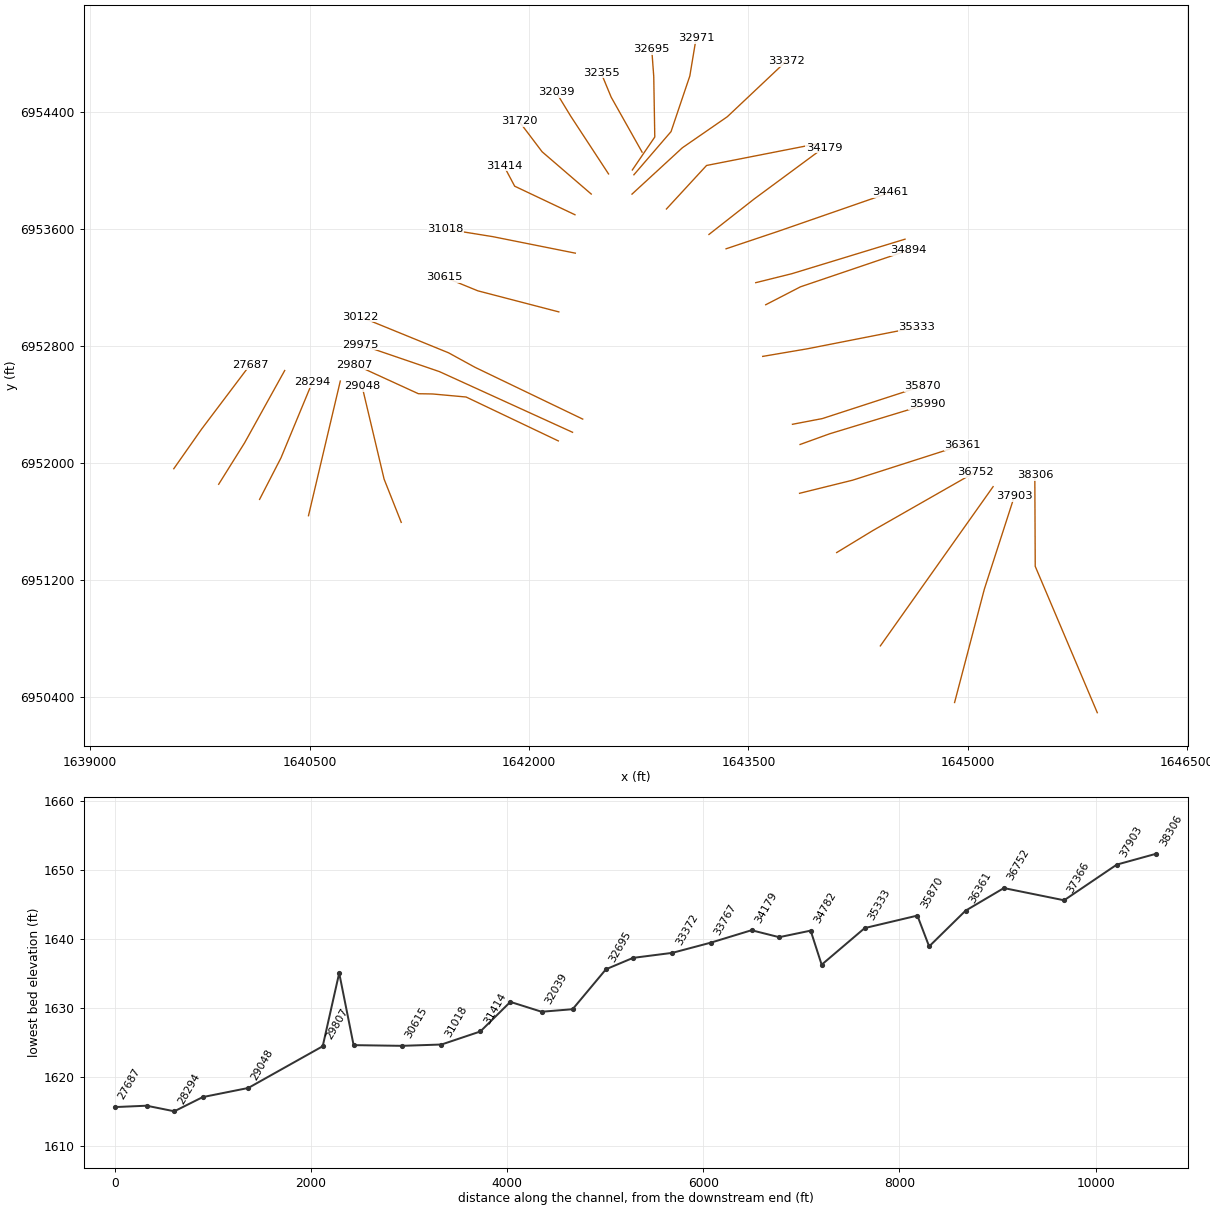
HEC-RAS study Chimney Creek.prj: Chimney Creek Base Level Engineering

--- Chimney Creek.g01 (geometry) --- (continued)

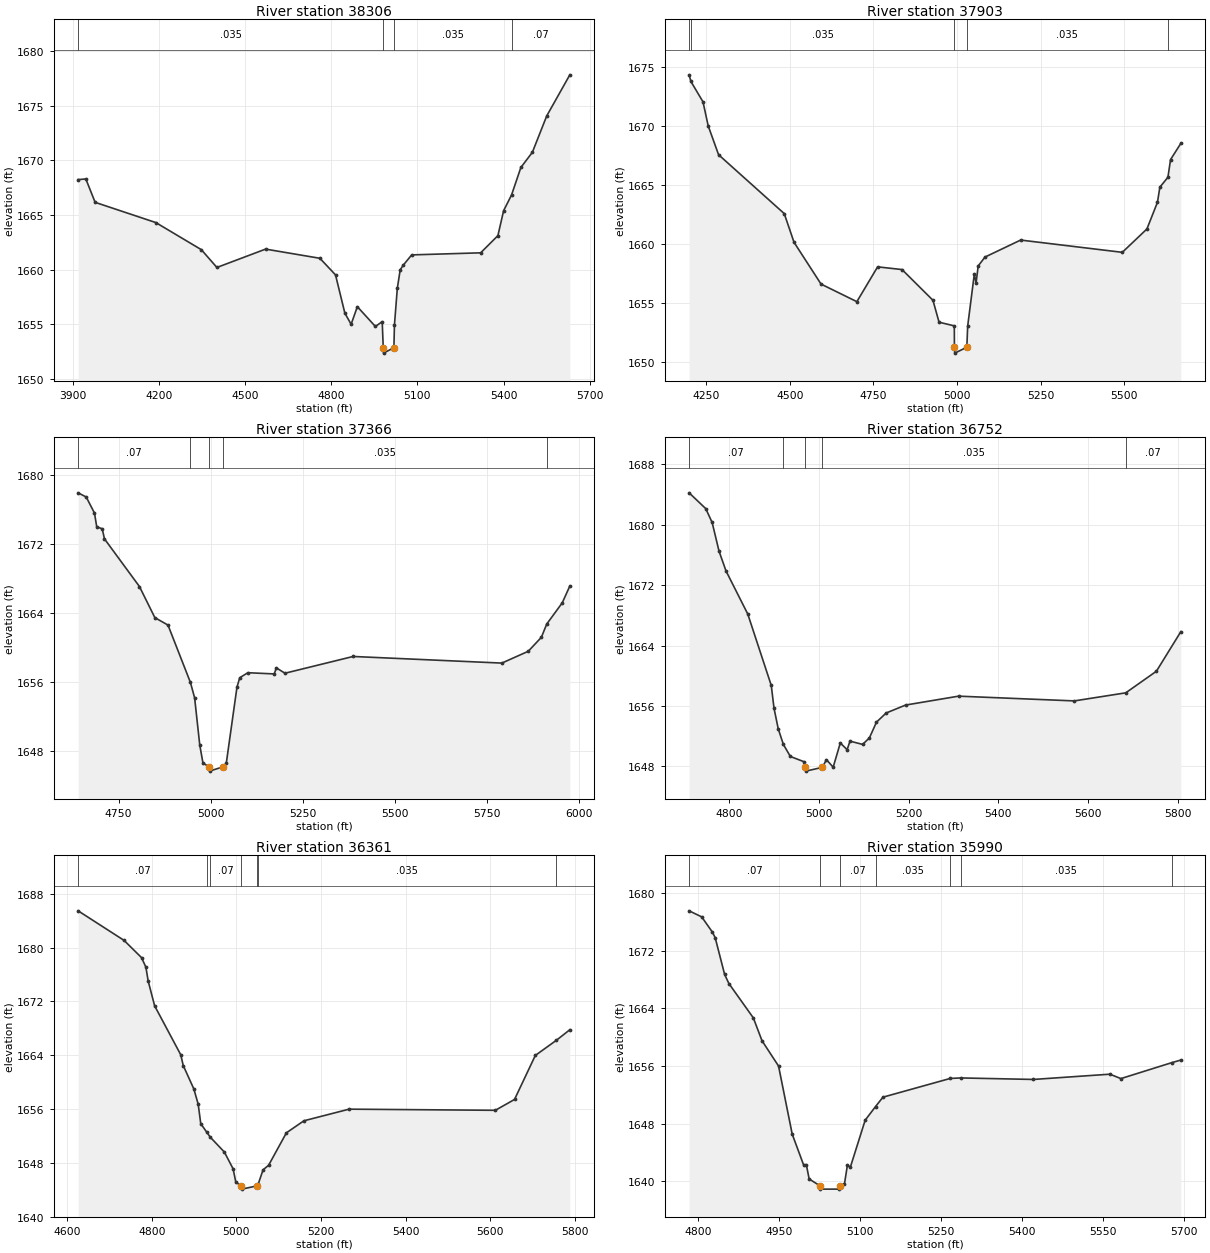
Type RM Length L Ch R = 1,38306,403,403,403
BEGIN DESCRIPTION:
Mapping XS c6a3fcbd
END DESCRIPTION:
XS GIS Cut Line= 3
      1645885.15      6950293.34      1645460.88      6951293.79
      1645458.07      6951918.38
#Sta/Elev= 30
  3919.5 1668.23  3946.3 1668.29  3978.7 1666.15  4189.8 1664.30  4348.2 1661.82
  4402.5 1660.19  4571.9 1661.87  4760.9 1661.03  4815.3 1659.51  4847.8 1656.01
  4869.6 1654.99  4891.3 1656.60  4954.1 1654.79  4977.8 1655.23  4981.4 1652.85
  4982.3 1652.35  5018.5 1652.85  5020.4 1654.93  5030.4 1658.29  5040.4 1659.97
  5050.4 1660.38  5080.4 1661.34  5320.4 1661.53  5380.4 1663.10  5400.4 1665.39
  5428.0 1666.83  5460.4 1669.34  5500.4 1670.73  5550.4 1674.06  5630.8 1677.82
#Mann=4,-1,0
  3919.5   0.035       0  4981.4   0.035       0  5018.5   0.035       0
  5428.0    0.07       0
Bank Sta=4981.4,5018.5
Exp/Cntr=0.3,0.1

Type RM Length L Ch R = 1,37903,537,537,537
BEGIN DESCRIPTION:
Mapping XS 437c863d
END DESCRIPTION:
XS GIS Cut Line= 3
      1644909.46      6950362.82      1645113.22      6951138.84
      1645318.71      6951774.53
#Sta/Elev= 30
  4199.0 1674.35  4204.3 1673.79  4240.5 1672.06  4256.0 1670.03  4287.1 1667.58
  4483.5 1662.59  4512.7 1660.16  4593.5 1656.62  4700.6 1655.13  4762.7 1658.08
  4835.7 1657.85  4928.1 1655.25  4946.4 1653.39  4992.0 1653.08  4992.4 1651.27
  4993.4 1650.77  5029.5 1651.27  5032.0 1653.06  5051.8 1657.46  5057.1 1656.72
  5063.5 1658.16  5083.8 1658.91  5190.4 1660.35  5494.4 1659.31  5568.0 1661.29
  5599.5 1663.55  5606.7 1664.83  5630.8 1665.67  5638.7 1667.17  5669.4 1668.54
#Mann=5,-1,0
  4199.0    0.07       0  4204.3   0.035       0  4992.4   0.035       0
  5029.5   0.035       0  5630.8    0.07       0
Bank Sta=4992.4,5029.5
Exp/Cntr=0.3,0.1

Type RM Length L Ch R = 1,37366,614,614,614
BEGIN DESCRIPTION:
Mapping XS a59f637a
END DESCRIPTION:
XS GIS Cut Line= 3
      1644402.01      6950750.03      1644612.05      6951046.87
      1645172.82      6951838.55
#Sta/Elev= 30
  4640.1 1677.98  4662.1 1677.49  4684.5 1675.62  4690.6 1674.02  4705.4 1673.80
  4711.6 1672.62  4806.4 1667.08  4848.2 1663.46  4883.9 1662.59  4944.7 1655.92
  4956.1 1654.13  4970.0 1648.65  4978.7 1646.54  4995.5 1646.10  4996.5 1645.60
  5033.2 1646.10  5041.9 1646.49  5071.0 1655.38  5078.6 1656.47  5100.5 1657.05
  5171.9 1656.91  5178.0 1657.61  5201.2 1656.99  5386.0 1658.94  5789.4 1658.17
  5861.0 1659.54  5896.7 1661.17  5911.2 1662.71  5953.3 1665.18  5973.9 1667.14
#Mann=5,-1,0
  4640.1    0.07       0  4944.7   0.035       0  4995.5   0.035       0
  5033.2   0.035       0  5911.2    0.07       0
Bank Sta=4995.5,5033.2
Exp/Cntr=0.3,0.1

Type RM Length L Ch R = 1,36752,391,391,391
BEGIN DESCRIPTION:
Mapping XS 91945e19
END DESCRIPTION:
XS GIS Cut Line= 3
      1644103.41      6951388.04      1644351.64      6951539.06
      1645050.65      6951938.00
#Sta/Elev= 30
  4711.0 1684.23  4748.0 1682.14  4762.3 1680.30  4777.7 1676.49  4793.2 1673.88
  4841.7 1668.17  4894.0 1658.72  4900.1 1655.71  4909.5 1652.98  4921.0 1650.90
  4936.6 1649.31  4967.6 1648.60  4970.0 1647.87  4971.0 1647.37  5007.8 1647.87
  5016.9 1648.89  5031.9 1647.89  5047.8 1651.10  5063.0 1650.21  5069.4 1651.34
  5097.5 1650.91  5112.6 1651.77  5128.4 1653.86  5150.0 1655.07  5193.2 1656.12
  5311.3 1657.30  5569.1 1656.67  5683.7 1657.74  5752.0 1660.60  5806.4 1665.84
#Mann=5,-1,0
  4711.0    0.07       0  4921.0   0.035       0  4970.0   0.035       0
  5007.8   0.035       0  5683.7    0.07       0
Bank Sta=4970,5007.8
Exp/Cntr=0.3,0.1

Type RM Length L Ch R = 1,36361,371,371,371
BEGIN DESCRIPTION:
Mapping XS 1970db4e
END DESCRIPTION:
XS GIS Cut Line= 3
      1643849.57      6951793.23      1644212.83      6951883.07
      1644962.62      6952123.47
#Sta/Elev= 30
  4626.1 1685.47  4734.7 1681.07  4775.9 1678.51  4786.2 1677.09  4791.6 1675.03
  4806.8 1671.35  4868.6 1664.06  4874.4 1662.47  4899.5 1658.98  4909.8 1656.70
  4915.8 1653.82  4930.4 1652.52  4938.2 1651.82  4971.6 1649.60  4992.2 1647.11
  4998.7 1645.10  5011.9 1644.59  5012.9 1644.09  5049.7 1644.59  5051.2 1644.78
  5063.0 1646.96  5076.1 1647.64  5118.1 1652.46  5159.4 1654.25  5266.2 1655.98
  5611.7 1655.81  5657.0 1657.42  5706.2 1663.97  5755.9 1666.22  5787.7 1667.79
#Mann=7,-1,0
  4626.1    0.07       0  4930.4   0.035       0  4938.2    0.07       0
  5011.9    0.07       0  5049.7    0.07       0  5051.2   0.035       0
  5755.9    0.07       0
Bank Sta=5011.9,5049.7
Exp/Cntr=0.3,0.1

Type RM Length L Ch R = 1,35990,120,120,120
BEGIN DESCRIPTION:
Mapping XS 79581d95
END DESCRIPTION:
XS GIS Cut Line= 3
      1643853.11      6952127.10      1644054.89      6952200.00
      1644721.21      6952402.62
#Sta/Elev= 30
  4783.9 1677.53  4807.2 1676.69  4826.9 1674.59  4832.2 1673.80  4849.7 1668.70
  4857.6 1667.44  4902.9 1662.67  4918.9 1659.51  4949.6 1655.99  4974.9 1646.54
  4995.9 1642.29  5001.1 1642.29  5006.3 1640.32  5025.5 1639.41  5026.5 1638.91
  5062.3 1638.91  5063.3 1639.41  5071.7 1639.62  5077.2 1642.26  5082.5 1641.93
  5110.1 1648.48  5129.3 1650.37  5143.0 1651.67  5267.7 1654.27  5287.3 1654.34
  5421.6 1654.13  5563.5 1654.86  5583.9 1654.25  5678.5 1656.47  5694.9 1656.82
#Mann=7,-1,0
  4783.9    0.07       0  5025.5    0.07       0  5063.3    0.07       0
  5129.3   0.035       0  5267.7    0.07       0  5287.3   0.035       0
  5678.5    0.07       0
Bank Sta=5025.5,5063.3
Exp/Cntr=0.3,0.1

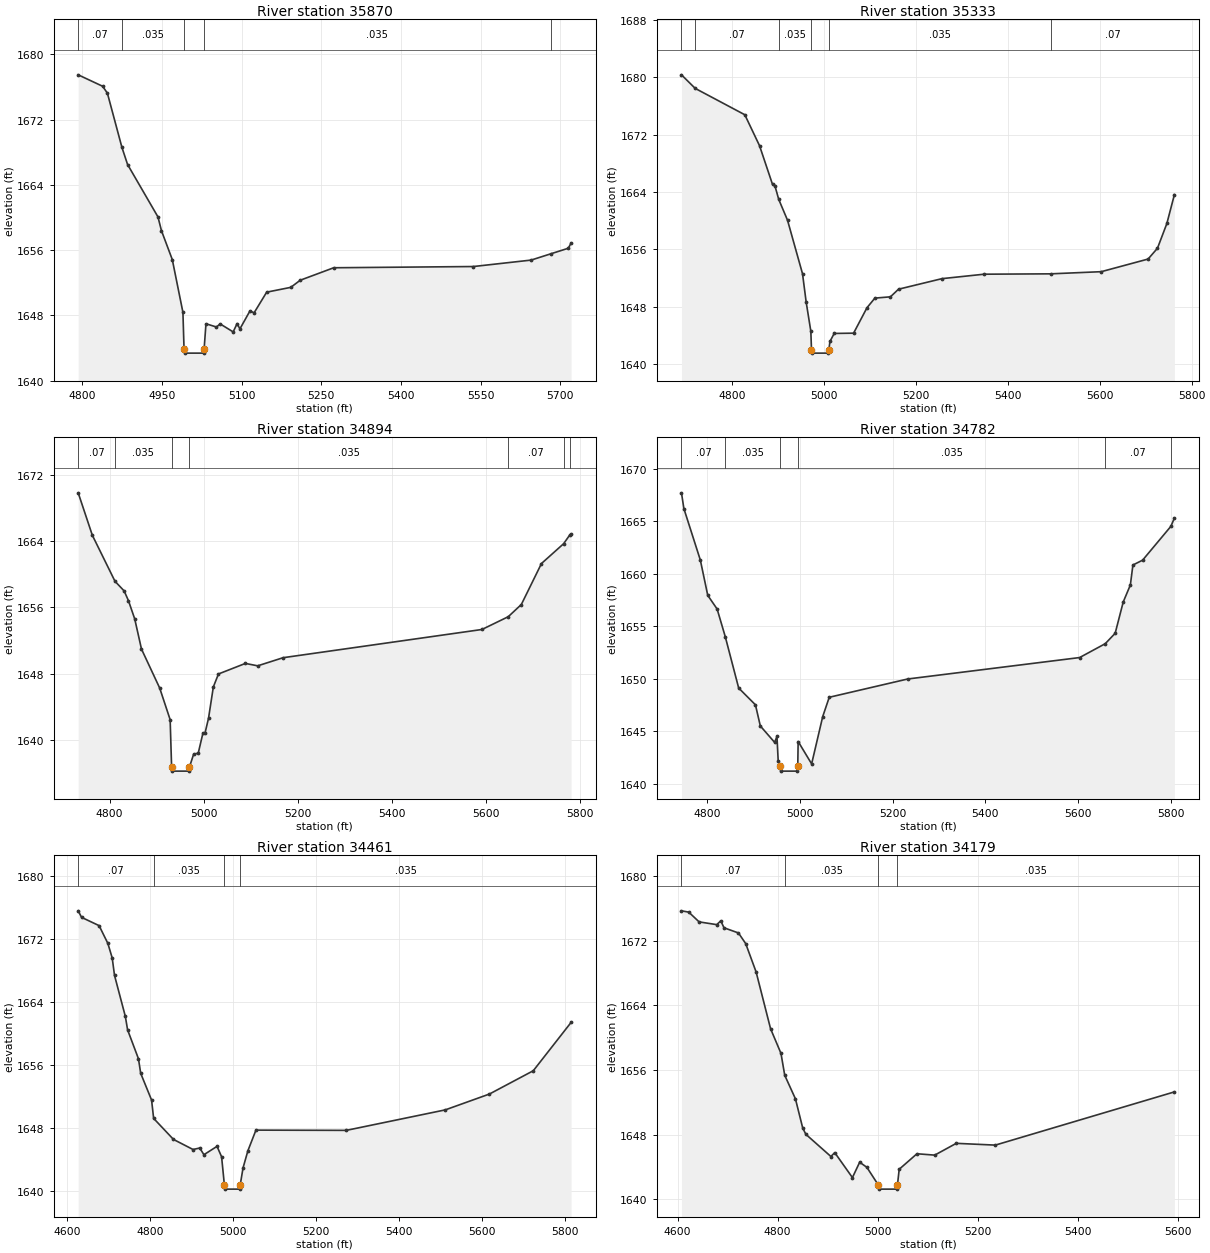
Type RM Length L Ch R = 1,35870,537,537,537
BEGIN DESCRIPTION:
Mapping XS 3e84752f
END DESCRIPTION:
XS GIS Cut Line= 3
      1643800.98      6952265.10      1644005.41      6952304.16
      1644690.11      6952526.76
#Sta/Elev= 30
  4792.2 1677.48  4838.2 1676.08  4847.2 1675.23  4874.5 1668.60  4885.2 1666.49
  4942.4 1660.07  4949.0 1658.38  4969.4 1654.84  4989.4 1648.38  4991.5 1643.88
  4992.5 1643.38  5028.3 1643.38  5029.3 1643.88  5032.8 1646.98  5052.5 1646.58
  5059.5 1646.96  5084.0 1645.98  5091.4 1647.00  5096.7 1646.35  5115.6 1648.55
  5123.4 1648.32  5147.1 1650.85  5192.5 1651.44  5210.2 1652.31  5273.3 1653.84
  5536.2 1653.99  5645.0 1654.78  5681.6 1655.54  5714.9 1656.23  5720.3 1656.87
#Mann=5,-1,0
  4792.2    0.07       0  4874.5   0.035       0  4991.5   0.035       0
  5029.3   0.035       0  5681.6    0.07       0
Bank Sta=4991.5,5029.3
Exp/Cntr=0.3,0.1

Type RM Length L Ch R = 1,35333,439,439,439
BEGIN DESCRIPTION:
Mapping XS a5bc224d
END DESCRIPTION:
XS GIS Cut Line= 3
      1643597.60      6952729.30      1643903.59      6952781.38
      1644651.10      6952928.28
#Sta/Elev= 30
  4690.3 1680.32  4720.2 1678.43  4828.1 1674.76  4860.1 1670.45  4888.3 1665.07
  4893.4 1664.90  4901.9 1662.97  4921.0 1660.07  4953.6 1652.62  4961.5 1648.70
  4971.7 1644.61  4973.1 1642.07  4974.0 1641.57  5009.9 1641.57  5010.9 1642.07
  5013.3 1643.20  5022.5 1644.31  5064.7 1644.35  5093.8 1647.89  5111.0 1649.23
  5144.8 1649.41  5162.4 1650.47  5256.9 1651.94  5348.6 1652.56  5493.4 1652.61
  5603.4 1652.91  5705.3 1654.67  5725.7 1656.18  5746.1 1659.62  5762.5 1663.64
#Mann=6,-1,0
  4690.3   0.035       0  4720.2    0.07       0  4901.9   0.035       0
  4973.1   0.035       0  5010.9   0.035       0  5493.4    0.07       0
Bank Sta=4973.1,5010.9
Exp/Cntr=0.3,0.1

Type RM Length L Ch R = 1,34894,112,112,112
BEGIN DESCRIPTION:
Mapping XS 9f7ad3ed
END DESCRIPTION:
XS GIS Cut Line= 3
      1643618.27      6953082.46      1643855.92      6953205.08
      1644594.62      6953455.45
#Sta/Elev= 30
  4733.1 1669.80  4763.2 1664.68  4811.3 1659.14  4830.7 1657.98  4839.8 1656.82
  4853.2 1654.61  4867.6 1650.97  4906.3 1646.27  4928.5 1642.46  4931.6 1636.76
  4932.6 1636.26  4968.6 1636.26  4969.6 1636.76  4978.4 1638.30  4988.2 1638.43
  4998.3 1640.87  5002.7 1640.87  5010.1 1642.65  5020.3 1646.41  5031.2 1647.97
  5088.4 1649.24  5114.5 1648.95  5168.5 1649.93  5591.0 1653.33  5646.9 1654.87
  5674.7 1656.34  5717.5 1661.28  5764.6 1663.67  5777.5 1664.71  5780.5 1664.79
#Mann=7,-1,0
  4733.1    0.07       0  4811.3   0.035       0  4931.6   0.035       0
  4969.6   0.035       0  5646.9    0.07       0  5764.6   0.035       0
  5777.5    0.07       0
Bank Sta=4931.6,4969.6
Exp/Cntr=0.3,0.1

Type RM Length L Ch R = 1,34782,321,321,321
BEGIN DESCRIPTION:
Mapping XS f90b5864
END DESCRIPTION:
XS GIS Cut Line= 4
      1643549.96      6953233.30      1643755.01      6953284.29
      1643798.41      6953295.14      1644570.62      6953530.80
#Sta/Elev= 30
  4744.6 1667.69  4749.8 1666.19  4785.3 1661.29  4801.3 1657.93  4821.5 1656.63
  4839.0 1654.01  4868.0 1649.11  4904.2 1647.51  4914.7 1645.50  4945.5 1643.94
  4950.6 1644.50  4953.3 1642.14  4957.5 1641.70  4958.5 1641.20  4994.5 1641.20
  4995.5 1641.70  4996.3 1644.02  5025.4 1641.89  5049.3 1646.39  5063.4 1648.23
  5232.7 1649.97  5603.5 1652.01  5658.8 1653.33  5680.2 1654.32  5697.6 1657.30
  5713.0 1658.92  5718.5 1660.82  5739.4 1661.28  5800.4 1664.50  5808.0 1665.29
#Mann=6,-1,0
  4744.6    0.07       0  4839.0   0.035       0  4957.5   0.035       0
  4995.5   0.035       0  5658.8    0.07       0  5800.4   0.035       0
Bank Sta=4957.5,4995.5
Exp/Cntr=0.3,0.1

Type RM Length L Ch R = 1,34461,282,282,282
BEGIN DESCRIPTION:
Mapping XS b0e1b639
END DESCRIPTION:
XS GIS Cut Line= 3
      1643347.24      6953465.06      1643703.10      6953584.40
      1644471.14      6953850.91
#Sta/Elev= 30
  4626.0 1675.58  4634.2 1674.75  4676.4 1673.70  4697.5 1671.45  4708.0 1669.60
  4713.6 1667.38  4739.7 1662.17  4745.1 1660.47  4771.3 1656.80  4776.7 1654.95
  4802.9 1651.56  4807.9 1649.23  4855.7 1646.56  4902.9 1645.28  4919.0 1645.47
  4929.1 1644.62  4960.7 1645.68  4971.7 1644.36  4978.5 1640.75  4979.5 1640.25
  5015.5 1640.25  5016.5 1640.75  5023.4 1642.94  5035.1 1645.12  5054.5 1647.74
  5272.4 1647.71  5510.9 1650.31  5617.3 1652.32  5723.1 1655.28  5814.3 1661.42
#Mann=4,-1,0
  4626.0    0.07       0  4807.9   0.035       0  4978.5   0.035       0
  5016.5   0.035       0
Bank Sta=4978.5,5016.5
Exp/Cntr=0.3,0.1

Type RM Length L Ch R = 1,34179,412,412,412
BEGIN DESCRIPTION:
Mapping XS c8b9ec8d
END DESCRIPTION:
XS GIS Cut Line= 3
      1643230.00      6953563.00      1643538.58      6953805.08
      1644015.73      6954157.35
#Sta/Elev= 30
  4607.8 1675.72  4622.3 1675.56  4643.1 1674.35  4678.3 1674.01  4686.4 1674.48
  4692.8 1673.62  4721.7 1672.98  4736.2 1671.66  4757.0 1668.15  4785.9 1661.12
  4806.7 1658.07  4814.2 1655.36  4835.6 1652.44  4850.1 1648.84  4856.4 1648.05
  4906.5 1645.30  4914.2 1645.78  4949.5 1642.69  4964.0 1644.59  4978.4 1643.96
  5001.4 1641.76  5002.4 1641.26  5038.5 1641.26  5039.5 1641.76  5043.0 1643.72
  5078.5 1645.64  5114.0 1645.47  5157.1 1646.93  5235.1 1646.71  5593.1 1653.30
#Mann=4,-1,0
  4607.8    0.07       0  4814.2   0.035       0  5001.4   0.035       0
  5039.5   0.035       0
Bank Sta=5001.4,5039.5
Exp/Cntr=0.3,0.1

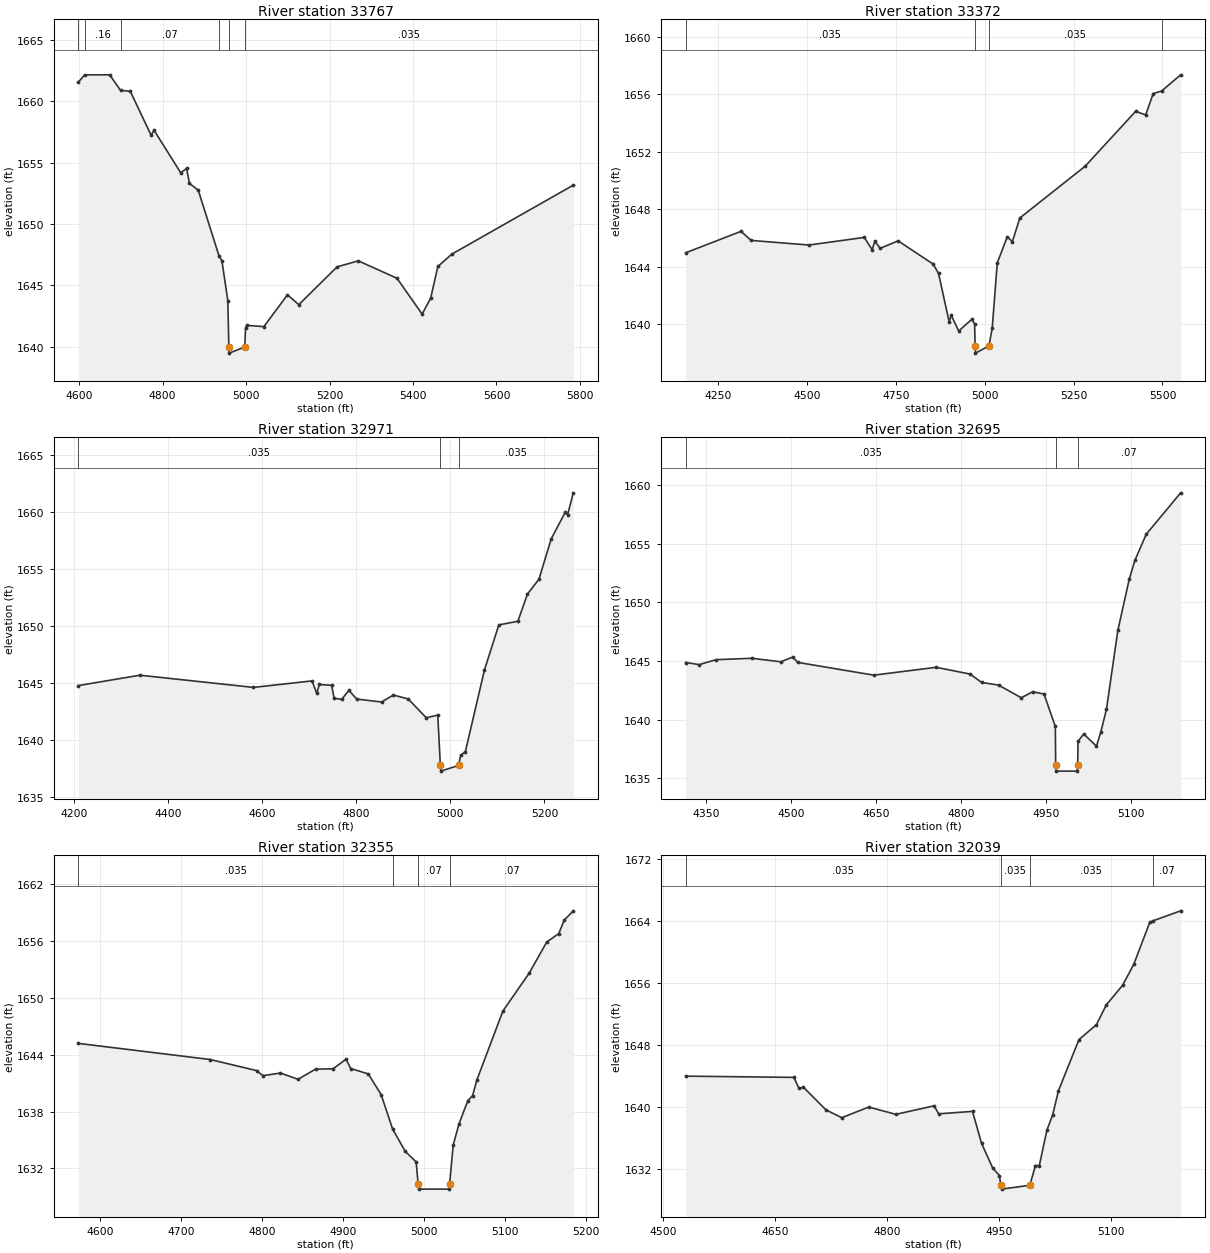
Type RM Length L Ch R = 1,33767,395,395,395
BEGIN DESCRIPTION:
Mapping XS a6f260d3
END DESCRIPTION:
XS GIS Cut Line= 3
      1642939.34      6953737.20      1643213.53      6954034.70
      1643980.55      6954185.06
#Sta/Elev= 30
  4597.9 1661.54  4613.2 1662.15  4673.2 1662.15  4699.1 1660.88  4722.5 1660.81
  4772.5 1657.22  4779.3 1657.64  4843.3 1654.17  4857.4 1654.52  4864.3 1653.30
  4885.3 1652.75  4935.5 1647.35  4942.0 1647.01  4956.2 1643.75  4958.7 1639.97
  4959.7 1639.47  4996.8 1639.97  4998.7 1641.53  5001.3 1641.73  5042.6 1641.63
  5099.2 1644.22  5126.3 1643.42  5218.0 1646.50  5268.9 1646.99  5361.6 1645.57
  5421.8 1642.65  5442.2 1643.94  5459.5 1646.53  5493.1 1647.54  5784.1 1653.16
#Mann=6,-1,0
  4597.9    0.07       0  4613.2    0.16       0  4699.1    0.07       0
  4935.5   0.035       0  4958.7   0.035       0  4996.8   0.035       0
Bank Sta=4958.7,4996.8
Exp/Cntr=0.3,0.1

Type RM Length L Ch R = 1,33372,401,401,401
BEGIN DESCRIPTION:
Mapping XS f6cba980
END DESCRIPTION:
XS GIS Cut Line= 4
      1642703.90      6953838.81      1643048.29      6954155.66
      1643355.37      6954367.80      1643756.42      6954745.93
#Sta/Elev= 30
  4158.8 1644.96  4314.6 1646.45  4343.0 1645.82  4505.7 1645.50  4661.3 1646.03
  4683.5 1645.17  4691.0 1645.77  4705.9 1645.27  4756.5 1645.79  4855.3 1644.17
  4870.2 1643.52  4899.9 1640.17  4906.0 1640.61  4926.9 1639.52  4963.1 1640.32
  4971.6 1640.03  4973.1 1638.48  4974.1 1637.98  5011.9 1638.48  5021.1 1639.70
  5035.3 1644.25  5063.6 1646.08  5077.8 1645.73  5098.8 1647.38  5282.9 1650.99
  5424.5 1654.80  5452.8 1654.55  5473.9 1656.03  5497.8 1656.22  5551.2 1657.34
#Mann=4,-1,0
  4158.8   0.035       0  4973.1   0.035       0  5011.9   0.035       0
  5497.8    0.07       0
Bank Sta=4973.1,5011.9
Exp/Cntr=0.3,0.1

Type RM Length L Ch R = 1,32971,276,276,276
BEGIN DESCRIPTION:
Mapping XS ee1768a1
END DESCRIPTION:
XS GIS Cut Line= 4
      1642716.94      6953971.21      1642970.84      6954266.34
      1643099.17      6954646.44      1643142.13      6954904.19
#Sta/Elev= 30
  4209.5 1644.75  4340.3 1645.66  4581.7 1644.59  4706.1 1645.16  4716.3 1644.06
  4721.6 1644.85  4747.8 1644.77  4753.1 1643.63  4769.4 1643.55  4784.5 1644.33
  4801.1 1643.57  4853.9 1643.31  4878.9 1643.92  4910.4 1643.58  4948.9 1641.93
  4973.3 1642.16  4978.8 1637.75  4979.8 1637.25  5017.6 1637.75  5021.9 1638.63
  5032.0 1638.97  5072.5 1646.12  5103.0 1650.07  5143.5 1650.39  5163.8 1652.77
  5188.3 1654.08  5214.5 1657.63  5244.1 1659.94  5249.2 1659.73  5261.3 1661.65
#Mann=3,-1,0
  4209.5   0.035       0  4978.8   0.035       0  5017.6   0.035       0
Bank Sta=4978.8,5017.6
Exp/Cntr=0.3,0.1

Type RM Length L Ch R = 1,32695,340,340,340
BEGIN DESCRIPTION:
Mapping XS 843f90ff
END DESCRIPTION:
XS GIS Cut Line= 4
      1642706.10      6954003.79      1642859.65      6954229.26
      1642852.63      6954642.01      1642838.93      6954828.41
#Sta/Elev= 30
  4314.4 1644.87  4338.4 1644.69  4367.9 1645.11  4431.2 1645.23  4482.0 1644.93
  4503.0 1645.33  4511.9 1644.88  4645.9 1643.79  4756.0 1644.46  4816.0 1643.88
  4836.0 1643.17  4866.0 1642.94  4906.0 1641.86  4926.0 1642.37  4946.0 1642.18
  4966.0 1639.41  4966.6 1636.10  4967.6 1635.60  5004.4 1635.60  5005.4 1636.10
  5006.0 1638.14  5016.0 1638.77  5038.5 1637.73  5046.1 1638.93  5056.1 1640.87
  5076.2 1647.61  5096.2 1651.97  5106.3 1653.59  5126.3 1655.82  5186.9 1659.35
#Mann=3,-1,0
  4314.4   0.035       0  4966.6    0.07       0  5005.4    0.07       0
Bank Sta=4966.6,5005.4
Exp/Cntr=0.3,0.1

Type RM Length L Ch R = 1,32355,316,316,316
BEGIN DESCRIPTION:
Mapping XS 700c4e09
END DESCRIPTION:
XS GIS Cut Line= 3
      1642772.71      6954126.13      1642561.58      6954501.63
      1642492.56      6954668.32
#Sta/Elev= 30
  4573.0 1645.19  4735.8 1643.49  4793.1 1642.32  4800.9 1641.78  4822.6 1642.06
  4844.3 1641.40  4865.9 1642.47  4887.6 1642.51  4903.6 1643.52  4909.3 1642.54
  4931.0 1641.97  4946.9 1639.79  4961.1 1636.15  4976.7 1633.79  4990.2 1632.68
  4992.6 1630.31  4993.6 1629.81  5030.4 1629.81  5031.4 1630.31  5035.9 1634.47
  5043.2 1636.73  5054.0 1639.16  5059.8 1639.67  5065.2 1641.35  5097.3 1648.61
  5129.7 1652.60  5151.4 1655.89  5166.2 1656.77  5173.0 1658.20  5184.2 1659.18
#Mann=4,-1,0
  4573.0   0.035       0  4961.1    0.07       0  4992.6    0.07       0
  5031.4    0.07       0
Bank Sta=4992.6,5031.4
Exp/Cntr=0.3,0.1

Type RM Length L Ch R = 1,32039,319,319,319
BEGIN DESCRIPTION:
Mapping XS 142a36ee
END DESCRIPTION:
XS GIS Cut Line= 3
      1642543.52      6953976.85      1642284.24      6954372.72
      1642186.01      6954534.28
#Sta/Elev= 30
  4530.6 1643.99  4675.4 1643.83  4682.2 1642.42  4688.2 1642.56  4718.4 1639.64
  4739.5 1638.64  4775.7 1640.01  4811.8 1639.07  4863.1 1640.17  4869.1 1639.14
  4914.4 1639.45  4926.5 1635.34  4941.5 1632.14  4950.4 1631.19  4952.2 1629.94
  4953.2 1629.44  4991.1 1629.94  4998.6 1632.48  5003.8 1632.48  5013.9 1637.01
  5021.7 1639.02  5029.4 1642.11  5056.8 1648.69  5080.2 1650.62  5093.4 1653.16
  5115.3 1655.70  5130.2 1658.40  5151.5 1663.78  5155.5 1663.98  5192.9 1665.28
#Mann=4,-1,0
  4530.6   0.035       0  4952.2   0.035       0  4991.1   0.035       0
  5155.5    0.07       0
Bank Sta=4952.2,4991.1
Exp/Cntr=0.3,0.1

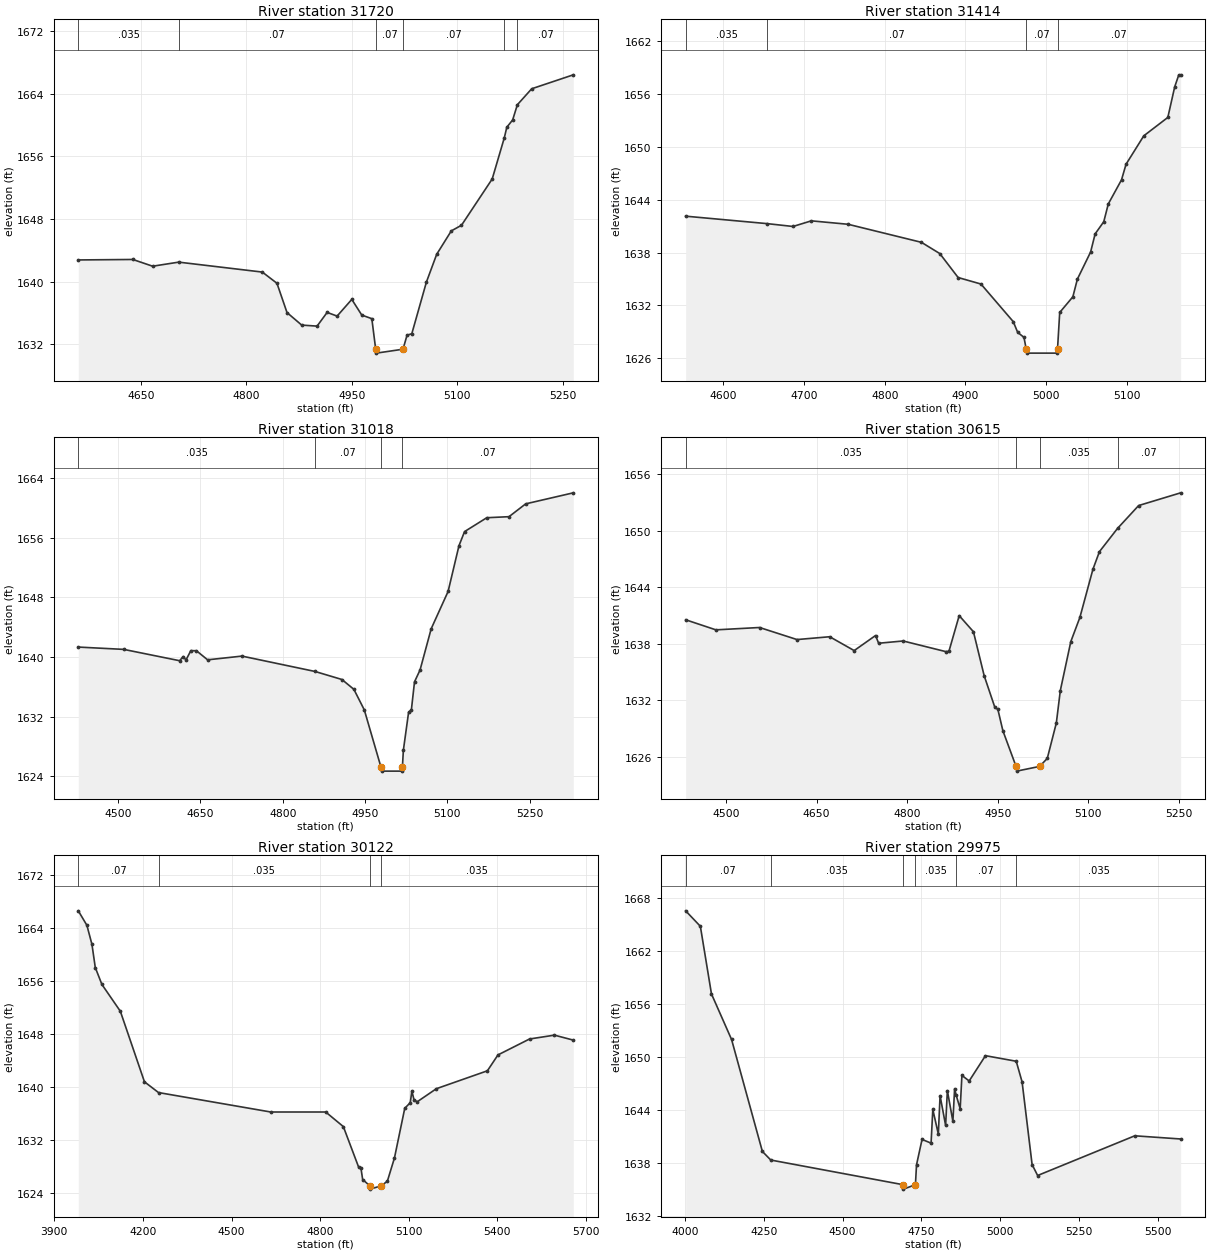
Type RM Length L Ch R = 1,31720,306,306,306
BEGIN DESCRIPTION:
Mapping XS c46e1f73
END DESCRIPTION:
XS GIS Cut Line= 3
      1642425.18      6953839.31      1642089.25      6954128.37
      1641931.68      6954336.72
#Sta/Elev= 30
  4560.7 1642.77  4638.3 1642.83  4666.5 1641.97  4703.6 1642.49  4822.6 1641.22
  4843.4 1639.79  4857.7 1636.05  4878.6 1634.45  4900.5 1634.32  4914.8 1636.07
  4929.0 1635.60  4949.9 1637.73  4964.1 1635.73  4978.4 1635.27  4983.9 1631.37
  4984.9 1630.87  5022.8 1631.37  5028.5 1633.16  5035.3 1633.35  5056.1 1639.95
  5070.7 1643.49  5091.5 1646.48  5106.0 1647.20  5149.7 1653.11  5166.9 1658.36
  5170.5 1659.72  5178.8 1660.65  5185.5 1662.59  5205.9 1664.63  5265.1 1666.41
#Mann=6,-1,0
  4560.7   0.035       0  4703.6    0.07       0  4983.9    0.07       0
  5022.8    0.07       0  5166.9   0.035       0  5185.5    0.07       0
Bank Sta=4983.9,5022.8
Exp/Cntr=0.3,0.1

Type RM Length L Ch R = 1,31414,396,396,396
BEGIN DESCRIPTION:
Mapping XS 854bcf12
END DESCRIPTION:
XS GIS Cut Line= 3
      1642313.95      6953697.82      1641901.64      6953893.12
      1641827.85      6954032.02
#Sta/Elev= 30
  4553.3 1642.14  4654.7 1641.29  4686.3 1640.97  4709.1 1641.61  4754.6 1641.22
  4845.5 1639.17  4868.3 1637.89  4891.0 1635.17  4919.3 1634.43  4959.3 1630.16
  4964.8 1628.94  4972.6 1628.37  4975.3 1627.08  4976.3 1626.58  5013.2 1626.58
  5014.2 1627.08  5016.9 1631.20  5033.2 1632.98  5038.8 1634.99  5055.2 1638.07
  5060.8 1640.13  5071.5 1641.51  5077.1 1643.53  5093.5 1646.27  5099.1 1648.04
  5121.1 1651.27  5150.9 1653.36  5159.4 1656.83  5164.5 1658.20  5166.8 1658.20
#Mann=4,-1,0
  4553.3   0.035       0  4654.7    0.07       0  4975.3    0.07       0
  5014.2    0.07       0
Bank Sta=4975.3,5014.2
Exp/Cntr=0.3,0.1

Type RM Length L Ch R = 1,31018,403,403,403
BEGIN DESCRIPTION:
Mapping XS 2f514460
END DESCRIPTION:
XS GIS Cut Line= 3
      1642316.15      6953435.22      1641751.90      6953548.07
      1641429.28      6953600.04
#Sta/Elev= 30
  4427.3 1641.33  4510.1 1641.02  4612.0 1639.50  4618.5 1640.06  4623.6 1639.60
  4632.4 1640.85  4642.6 1640.84  4663.0 1639.62  4725.6 1640.12  4858.7 1638.06
  4907.8 1636.98  4929.6 1635.66  4948.6 1632.90  4979.1 1625.19  4980.1 1624.69
  5017.0 1624.69  5018.0 1625.19  5019.8 1627.50  5029.3 1632.58  5034.4 1632.92
  5040.1 1636.67  5050.2 1638.26  5070.5 1643.79  5101.3 1648.79  5121.1 1654.92
  5131.3 1656.82  5171.8 1658.68  5212.3 1658.82  5242.7 1660.54  5329.5 1662.02
#Mann=4,-1,0
  4427.3   0.035       0  4858.7    0.07       0  4979.1    0.07       0
  5018.0    0.07       0
Bank Sta=4979.1,5018
Exp/Cntr=0.3,0.1

Type RM Length L Ch R = 1,30615,493,493,493
BEGIN DESCRIPTION:
Mapping XS 19621ffe
END DESCRIPTION:
XS GIS Cut Line= 3
      1642203.45      6953033.58      1641649.65      6953177.67
      1641420.52      6953271.41
#Sta/Elev= 30
  4433.1 1640.56  4483.2 1639.49  4555.5 1639.74  4617.5 1638.46  4671.7 1638.76
  4712.2 1637.29  4747.6 1638.89  4752.7 1638.07  4793.3 1638.31  4864.0 1637.18
  4869.1 1637.21  4886.1 1641.00  4909.7 1639.29  4927.5 1634.62  4945.0 1631.30
  4950.2 1631.04  4958.5 1628.78  4980.3 1625.00  4981.3 1624.50  5019.3 1625.00
  5032.0 1625.85  5047.0 1629.61  5053.6 1633.05  5071.0 1638.25  5086.0 1640.81
  5107.6 1645.92  5118.4 1647.79  5148.3 1650.25  5183.3 1652.68  5252.9 1654.03
#Mann=4,-1,0
  4433.1   0.035       0  4980.3   0.035       0  5019.3   0.035       0
  5148.3    0.07       0
Bank Sta=4980.3,5019.3
Exp/Cntr=0.3,0.1

Type RM Length L Ch R = 1,30122,147,147,147
BEGIN DESCRIPTION:
Mapping XS c99fae47
END DESCRIPTION:
XS GIS Cut Line= 4
      1642366.83      6952300.65      1641630.55      6952654.67
      1641449.99      6952753.63      1640845.82      6953000.16
#Sta/Elev= 30
  3981.4 1666.53  4010.5 1664.35  4027.6 1661.48  4038.9 1657.99  4061.3 1655.44
  4123.7 1651.40  4205.3 1640.77  4252.9 1639.15  4632.8 1636.22  4818.8 1636.22
  4878.5 1634.02  4930.1 1627.93  4938.2 1627.71  4943.9 1626.05  4968.0 1625.10
  4969.0 1624.60  5007.0 1625.10  5027.5 1625.80  5051.5 1629.30  5086.3 1636.77
  5105.0 1637.63  5110.4 1639.37  5117.7 1638.06  5128.5 1637.76  5193.3 1639.73
  5366.1 1642.43  5401.8 1644.82  5508.7 1647.22  5592.9 1647.80  5656.8 1647.05
#Mann=4,-1,0
  3981.4    0.07       0  4252.9   0.035       0  4968.0   0.035       0
  5007.0   0.035       0
Bank Sta=4968,5007
Exp/Cntr=0.3,0.1

Type RM Length L Ch R = 1,29975,168,168,168
BEGIN DESCRIPTION:
Mapping XS 535df2b4
END DESCRIPTION:
XS GIS Cut Line= 3
      1642297.37      6952210.38      1641387.49      6952625.15
      1640849.62      6952809.07
#Sta/Elev= 30
  4002.9 1666.52  4049.5 1664.77  4084.7 1657.12  4148.4 1651.97  4246.0 1639.31
  4272.6 1638.34  4691.9 1635.55  4692.9 1635.05  4730.9 1635.55  4734.4 1637.80
  4751.9 1640.67  4780.5 1640.25  4786.0 1644.06  4803.5 1641.27  4809.0 1645.62
  4826.6 1642.25  4832.1 1646.19  4849.6 1642.72  4855.1 1646.41  4859.9 1645.69
  4872.7 1644.14  4878.2 1647.91  4901.2 1647.28  4952.8 1650.14  5050.3 1649.51
  5068.9 1647.17  5100.6 1637.83  5118.1 1636.59  5425.9 1641.08  5571.3 1640.72
#Mann=6,-1,0
  4002.9    0.07       0  4272.6   0.035       0  4691.9    0.07       0
  4730.9   0.035       0  4859.9    0.07       0  5050.3   0.035       0
Bank Sta=4691.9,4730.9
Exp/Cntr=0.3,0.1

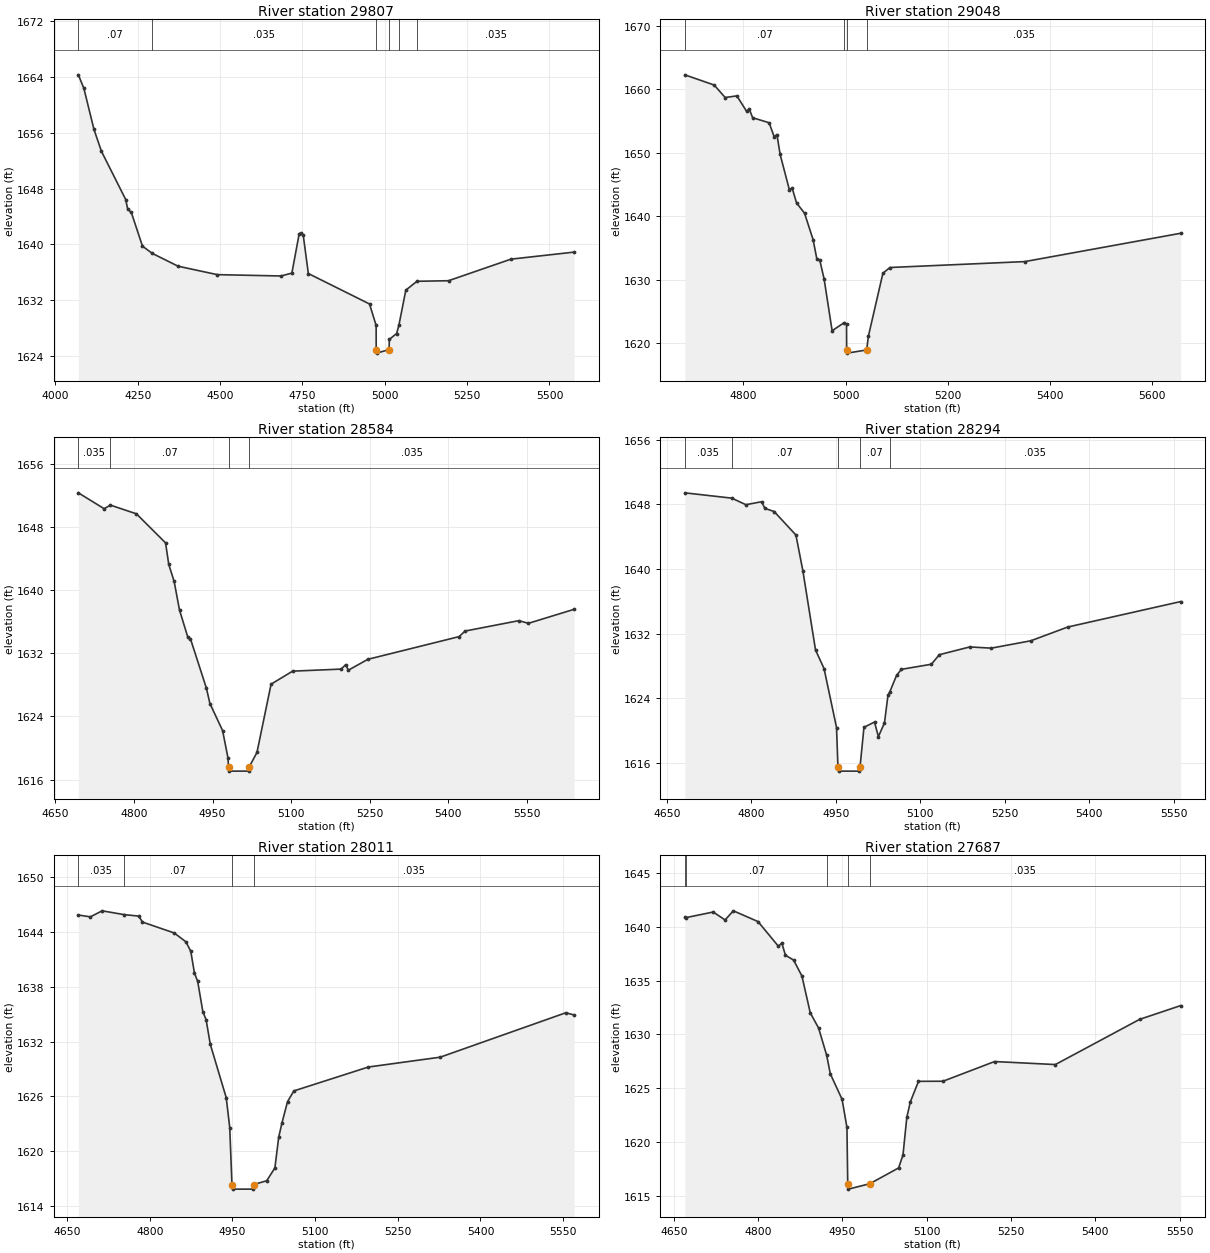
Type RM Length L Ch R = 1,29807,759,759,759
BEGIN DESCRIPTION:
Mapping XS d933e94d
END DESCRIPTION:
XS GIS Cut Line= 5
      1642200.18      6952151.34      1641569.78      6952451.54
      1641340.62      6952472.38      1641243.40      6952474.11
      1640807.63      6952673.77
#Sta/Elev= 30
  4070.0 1664.30  4086.8 1662.37  4117.4 1656.49  4140.1 1653.35  4213.8 1646.44
  4219.7 1645.08  4230.8 1644.59  4264.7 1639.76  4294.3 1638.73  4372.7 1636.89
  4491.8 1635.68  4684.9 1635.49  4718.1 1635.90  4740.3 1641.53  4747.1 1641.66
  4752.6 1641.33  4768.1 1635.84  4953.8 1631.48  4973.9 1628.40  4974.1 1624.94
  4975.1 1624.44  5013.1 1624.94  5014.0 1626.41  5036.1 1627.25  5043.0 1628.45
  5064.0 1633.46  5097.8 1634.73  5193.6 1634.81  5383.1 1637.90  5574.9 1638.91
#Mann=6,-1,0
  4070.0    0.07       0  4294.3   0.035       0  4974.1   0.035       0
  5013.1   0.035       0  5043.0    0.07       0  5097.8   0.035       0
Bank Sta=4974.1,5013.1
Exp/Cntr=0.3,0.1

Type RM Length L Ch R = 1,29048,464,464,464
BEGIN DESCRIPTION:
Mapping XS ae934f3d
END DESCRIPTION:
XS GIS Cut Line= 3
      1641126.09      6951594.57      1641008.91      6951890.13
      1640858.34      6952524.87
#Sta/Elev= 30
  4685.2 1662.30  4742.7 1660.69  4764.2 1658.72  4787.1 1658.98  4806.0 1656.56
  4811.4 1656.89  4818.0 1655.53  4850.2 1654.74  4860.1 1652.53  4865.5 1652.87
  4871.8 1649.73  4889.8 1644.17  4895.2 1644.45  4904.0 1642.07  4919.5 1640.47
  4936.3 1636.29  4943.8 1633.17  4949.2 1633.11  4957.8 1630.10  4973.5 1621.92
  4997.3 1623.21  5001.7 1622.93  5001.9 1618.89  5002.9 1618.39  5041.1 1618.89
  5044.5 1621.07  5072.9 1631.00  5086.7 1631.90  5350.4 1632.83  5655.5 1637.30
#Mann=4,-1,0
  4685.2    0.07       0  4997.3   0.035       0  5001.9   0.035       0
  5041.1   0.035       0
Bank Sta=5001.9,5041.1
Exp/Cntr=0.3,0.1

Type RM Length L Ch R = 1,28584,290,290,290
BEGIN DESCRIPTION:
Mapping XS 8789b622
END DESCRIPTION:
XS GIS Cut Line= 3
      1640491.98      6951640.12      1640563.60      6951943.51
      1640709.43      6952560.68
#Sta/Elev= 30
  4694.0 1652.34  4743.2 1650.33  4755.3 1650.78  4804.8 1649.68  4860.4 1646.00
  4866.5 1643.27  4876.8 1641.11  4887.0 1637.49  4902.7 1634.08  4907.9 1633.84
  4938.4 1627.57  4945.0 1625.64  4969.2 1622.21  4979.5 1618.74  4980.5 1617.57
  4981.5 1617.07  5018.7 1617.07  5019.7 1617.57  5034.8 1619.44  5061.7 1628.09
  5102.8 1629.74  5195.3 1630.00  5204.0 1630.56  5209.1 1629.86  5246.3 1631.24
  5420.6 1634.12  5431.6 1634.82  5534.4 1636.14  5552.6 1635.80  5639.9 1637.58
#Mann=4,-1,0
  4694.0   0.035       0  4755.3    0.07       0  4980.5   0.035       0
  5019.7   0.035       0
Bank Sta=4980.5,5019.7
Exp/Cntr=0.3,0.1

Type RM Length L Ch R = 1,28294,283,283,283
BEGIN DESCRIPTION:
Mapping XS 767cc703
END DESCRIPTION:
XS GIS Cut Line= 3
      1640157.58      6951751.66      1640304.05      6952035.92
      1640518.56      6952553.77
#Sta/Elev= 30
  4682.1 1649.43  4765.7 1648.77  4790.5 1647.96  4818.5 1648.33  4824.2 1647.51
  4840.7 1647.12  4879.4 1644.21  4891.7 1639.80  4914.2 1629.99  4929.3 1627.70
  4951.5 1620.40  4954.0 1615.51  4955.0 1615.01  4992.2 1615.01  4993.2 1615.51
  5000.2 1620.43  5018.9 1621.08  5025.8 1619.28  5036.6 1620.97  5042.8 1624.38
  5045.8 1624.77  5058.2 1626.87  5066.7 1627.60  5119.9 1628.23  5134.0 1629.41
  5188.1 1630.37  5226.2 1630.22  5296.4 1631.13  5361.9 1632.83  5562.4 1635.98
#Mann=5,-1,0
  4682.1   0.035       0  4765.7    0.07       0  4954.0    0.07       0
  4993.2    0.07       0  5045.8   0.035       0
Bank Sta=4954,4993.2
Exp/Cntr=0.3,0.1

Type RM Length L Ch R = 1,28011,324,324,324
BEGIN DESCRIPTION:
Mapping XS 35a03b1a
END DESCRIPTION:
XS GIS Cut Line= 3
      1639877.92      6951855.10      1640054.99      6952138.06
      1640329.28      6952632.82
#Sta/Elev= 30
  4670.5 1645.88  4692.4 1645.68  4713.7 1646.34  4753.0 1645.93  4780.1 1645.76
  4786.8 1645.11  4844.5 1643.91  4865.7 1642.94  4874.5 1641.90  4881.1 1639.53
  4887.0 1638.61  4896.4 1635.28  4902.3 1634.40  4909.9 1631.70  4938.8 1625.85
  4945.2 1622.56  4949.2 1616.32  4950.2 1615.82  4987.4 1615.82  4988.4 1616.32
  5012.3 1616.74  5027.1 1618.15  5034.0 1621.51  5039.8 1623.05  5050.0 1625.41
  5061.5 1626.59  5196.6 1629.21  5327.0 1630.29  5554.8 1635.16  5570.0 1634.92
#Mann=4,-1,0
  4670.5   0.035       0  4753.0    0.07       0  4949.2   0.035       0
  4988.4   0.035       0
Bank Sta=4949.2,4988.4
Exp/Cntr=0.3,0.1

Type RM Length L Ch R = 1,27687,287,287,287
BEGIN DESCRIPTION:
Mapping XS 7cf0c543
END DESCRIPTION:
XS GIS Cut Line= 3
      1639571.03      6951961.38      1639761.15      6952232.24
      1640093.17      6952672.32
#Sta/Elev= 30
  4669.5 1640.87  4671.7 1640.86  4720.1 1641.38  4741.1 1640.64  4755.9 1641.49
  4799.8 1640.49  4836.0 1638.20  4842.1 1638.49  4848.6 1637.36  4863.1 1636.91
  4877.9 1635.43  4892.7 1632.01  4907.5 1630.60  4921.9 1628.07  4928.4 1626.34
  4949.3 1623.97  4958.0 1621.36  4959.4 1616.12  4960.4 1615.62  4998.6 1616.12
  5049.9 1617.59  5057.7 1618.79  5064.5 1622.28  5070.7 1623.72  5085.3 1625.64
  5129.0 1625.65  5220.6 1627.48  5328.8 1627.20  5478.7 1631.40  5551.7 1632.68
#Mann=5,-1,0
  4669.5   0.035       0  4671.7    0.07       0  4921.9   0.035       0
  4959.4   0.035       0  4998.6   0.035       0
Bank Sta=4959.4,4998.6
Exp/Cntr=0.3,0.1