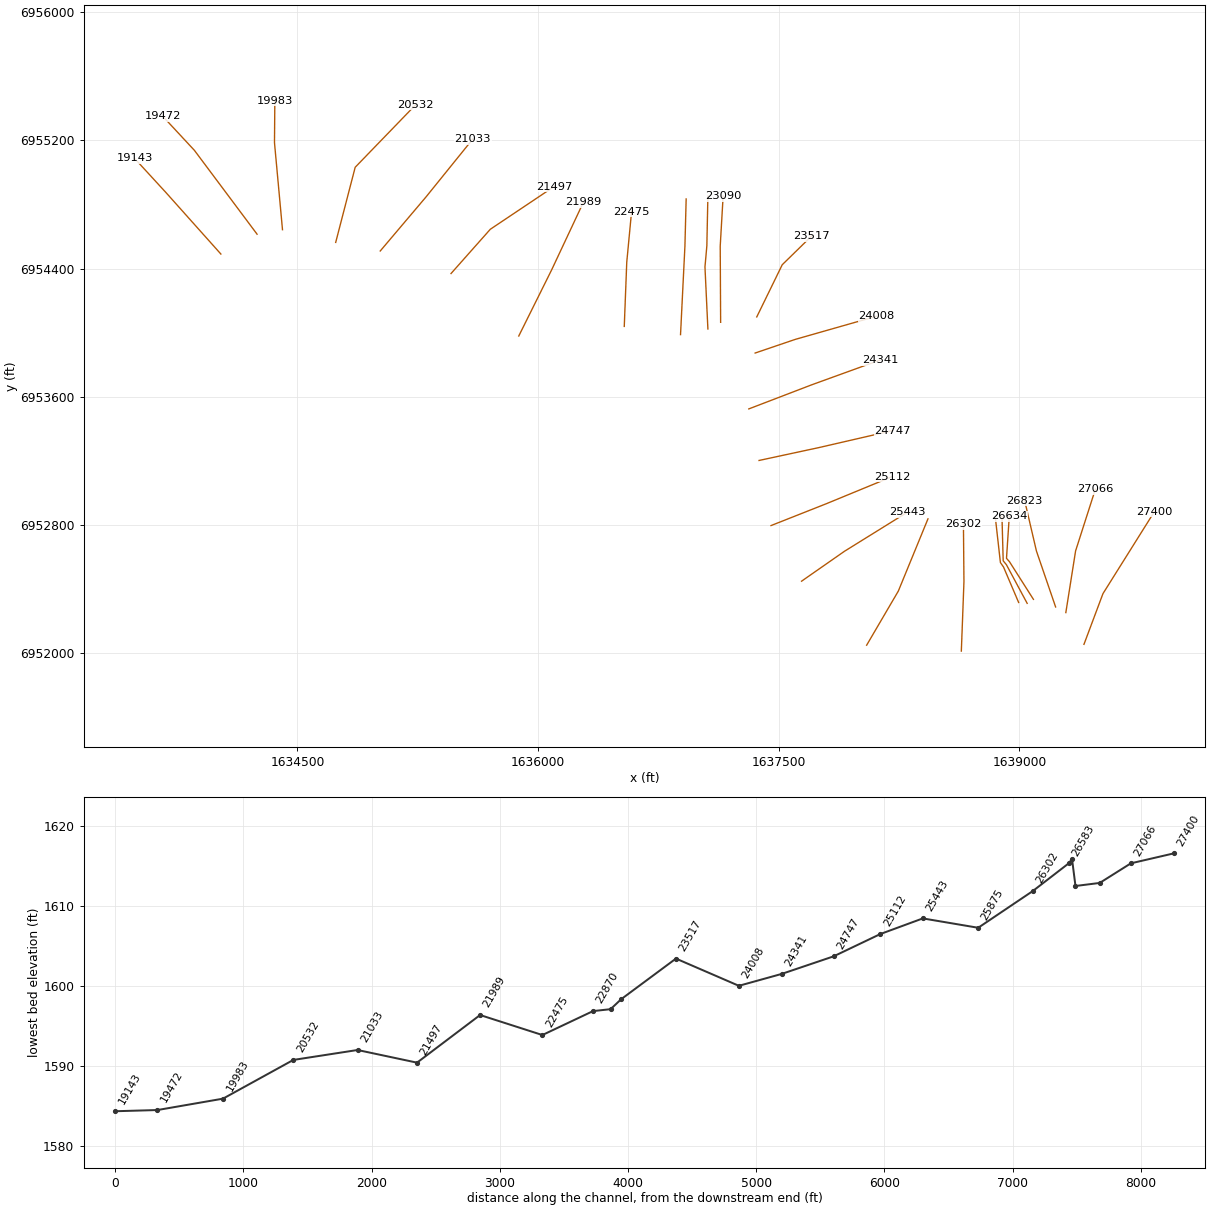
HEC-RAS study Chimney Creek.prj: Chimney Creek Base Level Engineering

--- Chimney Creek.g01 (geometry) --- (continued)

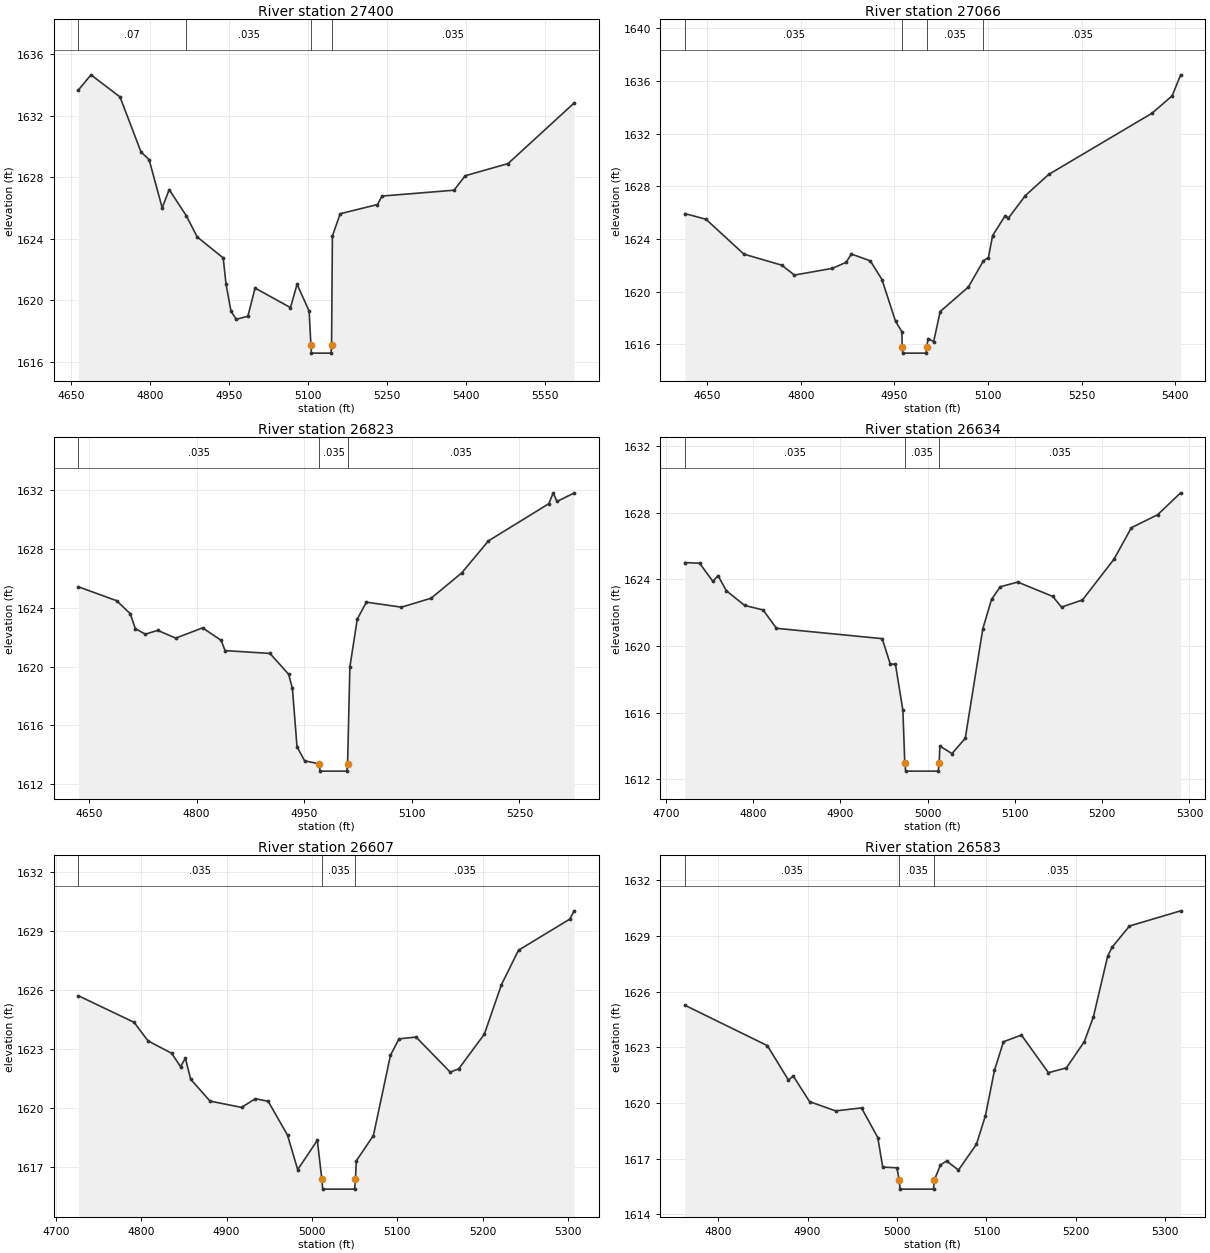
Type RM Length L Ch R = 1,27400,334,334,334
BEGIN DESCRIPTION:
Mapping XS bf7695ee
END DESCRIPTION:
XS GIS Cut Line= 3
      1639403.10      6952056.50      1639521.57      6952372.87
      1639842.27      6952884.43
#Sta/Elev= 30
  4663.9 1633.67  4687.9 1634.66  4743.1 1633.22  4783.0 1629.64  4798.3 1629.15
  4823.2 1626.01  4836.4 1627.20  4868.8 1625.51  4889.7 1624.12  4939.0 1622.76
  4944.3 1621.08  4953.8 1619.29  4963.9 1618.77  4985.9 1618.97  4999.5 1620.80
  5066.8 1619.53  5079.3 1621.05  5102.2 1619.30  5105.6 1617.07  5106.6 1616.57
  5143.8 1616.57  5144.8 1617.07  5146.4 1624.19  5161.2 1625.63  5232.0 1626.23
  5240.7 1626.78  5377.4 1627.16  5398.6 1628.10  5479.9 1628.89  5605.5 1632.83
#Mann=4,-1,0
  4663.9    0.07       0  4868.8   0.035       0  5105.6   0.035       0
  5144.8   0.035       0
Bank Sta=5105.6,5144.8
Exp/Cntr=0.3,0.1

Type RM Length L Ch R = 1,27066,243,243,243
BEGIN DESCRIPTION:
Mapping XS 7a659148
END DESCRIPTION:
XS GIS Cut Line= 3
      1639290.12      6952254.47      1639350.98      6952639.49
      1639474.44      6953024.79
#Sta/Elev= 30
  4614.2 1625.93  4648.1 1625.50  4708.9 1622.85  4769.6 1622.01  4789.9 1621.26
  4850.6 1621.77  4872.8 1622.23  4881.0 1622.86  4911.4 1622.34  4930.1 1620.92
  4951.9 1617.74  4962.0 1616.96  4962.5 1615.83  4963.5 1615.33  5000.9 1615.33
  5001.9 1615.83  5004.0 1616.44  5012.9 1616.20  5023.4 1618.49  5068.5 1620.35
  5092.7 1622.35  5100.6 1622.59  5107.4 1624.26  5127.5 1625.77  5132.8 1625.59
  5159.7 1627.29  5197.1 1628.90  5363.0 1633.56  5395.1 1634.88  5408.6 1636.47
#Mann=4,-1,0
  4614.2   0.035       0  4962.5    0.07       0  5001.9   0.035       0
  5092.7   0.035       0
Bank Sta=4962.5,5001.9
Exp/Cntr=0.3,0.1

Type RM Length L Ch R = 1,26823,189,189,189
BEGIN DESCRIPTION:
Mapping XS 4eea124f
END DESCRIPTION:
XS GIS Cut Line= 3
      1639226.32      6952289.64      1639106.84      6952638.40
      1639033.61      6952952.42
#Sta/Elev= 30
  4635.2 1625.44  4688.6 1624.49  4707.5 1623.61  4714.6 1622.59  4728.6 1622.21
  4745.9 1622.47  4770.9 1621.94  4808.4 1622.64  4834.3 1621.79  4839.7 1621.09
  4902.3 1620.90  4928.3 1619.48  4933.6 1618.52  4940.0 1614.54  4950.6 1613.58
  4971.1 1613.38  4972.1 1612.88  5009.5 1612.88  5010.5 1613.38  5013.7 1619.98
  5024.0 1623.24  5036.7 1624.39  5085.6 1624.05  5126.9 1624.66  5169.5 1626.38
  5206.9 1628.57  5291.0 1631.10  5297.1 1631.84  5302.3 1631.25  5326.3 1631.83
#Mann=3,-1,0
  4635.2   0.035       0  4971.1   0.035       0  5010.5   0.035       0
Bank Sta=4971.1,5010.5
Exp/Cntr=0.3,0.1

Type RM Length L Ch R = 1,26634,27,27,27
BEGIN DESCRIPTION:
Mapping XS 3de640db
END DESCRIPTION:
XS GIS Cut Line= 4
      1639088.13      6952337.13      1638938.74      6952571.93
      1638920.21      6952592.83      1638937.49      6952854.23
#Sta/Elev= 30
  4721.7 1625.00  4738.7 1624.96  4753.9 1623.87  4759.8 1624.22  4769.2 1623.32
  4790.3 1622.43  4811.5 1622.16  4826.7 1621.06  4947.9 1620.44  4957.1 1618.93
  4963.1 1618.90  4971.6 1616.15  4973.8 1613.00  4974.8 1612.50  5012.2 1612.50
  5013.2 1613.00  5014.0 1614.00  5027.9 1613.55  5043.1 1614.47  5063.2 1621.03
  5073.2 1622.79  5083.2 1623.55  5103.3 1623.83  5143.4 1622.97  5153.4 1622.33
  5177.4 1622.76  5213.5 1625.20  5233.5 1627.09  5263.6 1627.87  5289.9 1629.18
#Mann=3,-1,0
  4721.7   0.035       0  4973.8   0.035       0  5013.2   0.035       0
Bank Sta=4973.8,5013.2
Exp/Cntr=0.3,0.1

Type RM Length L Ch R = 1,26607,24,24,24
BEGIN DESCRIPTION:
Mapping XS 7def3620
END DESCRIPTION:
XS GIS Cut Line= 4
      1639049.12      6952312.09      1638919.70      6952553.14
      1638899.60      6952577.64      1638892.00      6952853.15
#Sta/Elev= 30
  4726.4 1625.70  4791.7 1624.35  4808.0 1623.41  4835.6 1622.78  4846.2 1622.10
  4851.8 1622.53  4858.0 1621.46  4880.7 1620.35  4917.6 1620.03  4933.8 1620.47
  4948.8 1620.34  4971.5 1618.62  4983.4 1616.87  5006.4 1618.36  5011.7 1616.38
  5012.7 1615.88  5050.1 1615.88  5051.1 1616.38  5052.1 1617.32  5072.1 1618.60
  5092.1 1622.68  5102.1 1623.51  5122.1 1623.60  5162.1 1621.82  5172.1 1621.99
  5202.1 1623.75  5222.1 1626.26  5242.1 1628.01  5302.2 1629.59  5307.3 1630.01
#Mann=3,-1,0
  4726.4   0.035       0  5011.7   0.035       0  5051.1   0.035       0
Bank Sta=5011.7,5051.1
Exp/Cntr=0.3,0.1

Type RM Length L Ch R = 1,26583,281,281,281
BEGIN DESCRIPTION:
Mapping XS a001fc05
END DESCRIPTION:
XS GIS Cut Line= 4
      1638995.93      6952317.55      1638901.77      6952538.58
      1638882.23      6952566.79      1638850.98      6952844.88
#Sta/Elev= 30
  4762.7 1625.27  4855.0 1623.09  4878.6 1621.23  4884.0 1621.45  4902.2 1620.07
  4931.3 1619.57  4960.3 1619.73  4978.5 1618.13  4984.0 1616.54  4999.9 1616.50
  5002.4 1615.85  5003.4 1615.35  5040.8 1615.35  5041.8 1615.85  5048.5 1616.65
  5055.4 1616.87  5068.7 1616.38  5088.8 1617.77  5098.9 1619.32  5108.9 1621.75
  5119.0 1623.30  5139.1 1623.66  5169.3 1621.63  5189.4 1621.89  5209.5 1623.31
  5219.6 1624.65  5235.5 1627.91  5240.5 1628.40  5259.9 1629.54  5317.1 1630.36
#Mann=3,-1,0
  4762.7   0.035       0  5002.4   0.035       0  5041.8   0.035       0
Bank Sta=5002.4,5041.8
Exp/Cntr=0.3,0.1

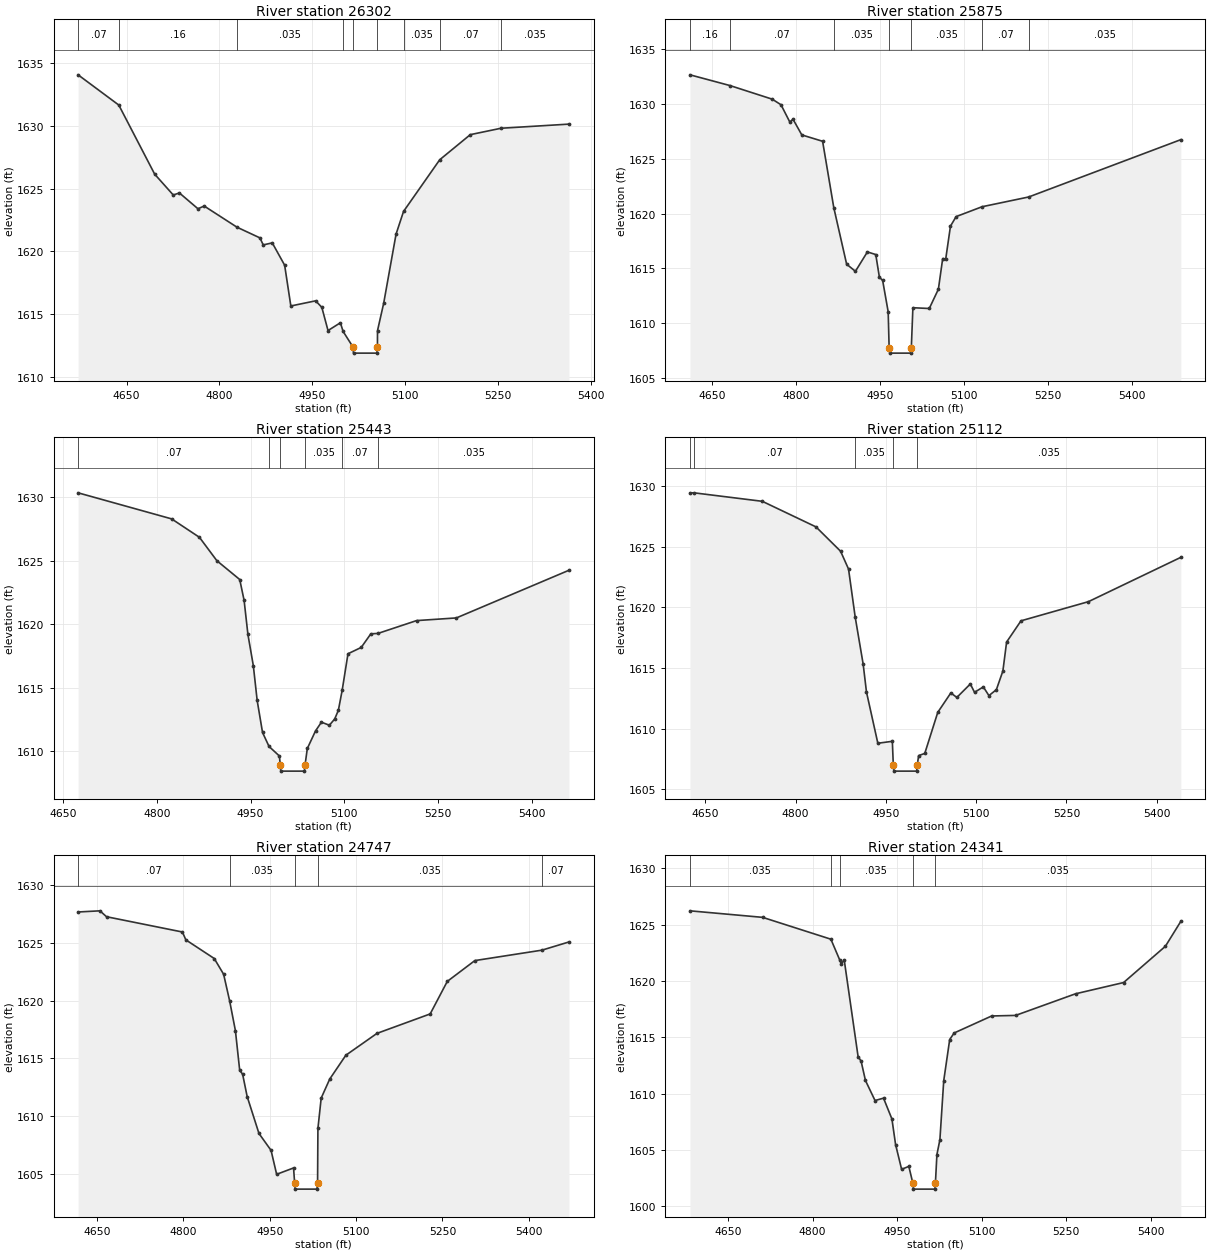
Type RM Length L Ch R = 1,26302,427,427,427
BEGIN DESCRIPTION:
Mapping XS 56fbaa73
END DESCRIPTION:
XS GIS Cut Line= 3
      1638638.74      6952014.30      1638655.02      6952447.25
      1638651.77      6952807.48
#Sta/Elev= 30
  4571.5 1634.07  4637.3 1631.66  4695.3 1626.15  4725.3 1624.49  4735.3 1624.65
  4765.3 1623.39  4775.3 1623.61  4828.4 1621.92  4865.4 1621.07  4870.8 1620.51
  4885.4 1620.67  4905.4 1618.89  4915.4 1615.64  4955.5 1616.05  4965.5 1615.53
  4975.5 1613.68  4995.5 1614.30  4999.9 1613.61  5015.7 1612.38  5016.7 1611.88
  5054.4 1611.88  5055.4 1612.38  5055.5 1613.67  5065.5 1615.86  5085.5 1621.37
  5097.6 1623.18  5156.1 1627.30  5205.5 1629.30  5255.1 1629.81  5365.0 1630.14
#Mann=9,-1,0
  4571.5    0.07       0  4637.3    0.16       0  4828.4   0.035       0
  4999.9    0.07       0  5015.7    0.07       0  5055.4    0.07       0
  5097.6   0.035       0  5156.1    0.07       0  5255.1   0.035       0
Bank Sta=5015.7,5055.4
Exp/Cntr=0.3,0.1

Type RM Length L Ch R = 1,25875,432,432,432
BEGIN DESCRIPTION:
Mapping XS 8e28cfe2
END DESCRIPTION:
XS GIS Cut Line= 3
      1638048.48      6952051.22      1638245.95      6952388.66
      1638430.73      6952839.27
#Sta/Elev= 30
  4610.3 1632.66  4681.9 1631.68  4757.4 1630.44  4773.1 1629.93  4788.8 1628.36
  4794.6 1628.61  4810.3 1627.18  4847.5 1626.60  4867.5 1620.55  4890.5 1615.39
  4906.2 1614.74  4927.6 1616.51  4942.6 1616.27  4949.1 1614.20  4954.9 1613.91
  4964.8 1611.05  4966.5 1607.78  4967.5 1607.28  5005.2 1607.28  5006.2 1607.78
  5009.0 1611.42  5038.3 1611.35  5054.6 1613.11  5062.3 1615.90  5067.7 1615.86
  5076.2 1618.86  5086.3 1619.73  5132.7 1620.63  5216.1 1621.52  5488.3 1626.75
#Mann=7,-1,0
  4610.3    0.16       0  4681.9    0.07       0  4867.5   0.035       0
  4966.5   0.035       0  5006.2   0.035       0  5132.7    0.07       0
  5216.1   0.035       0
Bank Sta=4966.5,5006.2
Exp/Cntr=0.3,0.1

Type RM Length L Ch R = 1,25443,331,331,331
BEGIN DESCRIPTION:
Mapping XS c2b1913b
END DESCRIPTION:
XS GIS Cut Line= 3
      1637642.76      6952450.40      1637909.69      6952636.59
      1638300.80      6952879.58
#Sta/Elev= 30
  4673.9 1630.34  4823.7 1628.29  4868.2 1626.84  4896.1 1625.00  4932.7 1623.52
  4939.7 1621.88  4945.8 1619.20  4954.5 1616.73  4960.6 1614.01  4969.2 1611.49
  4979.6 1610.39  4996.2 1609.64  4997.5 1608.95  4998.5 1608.45  5036.3 1608.45
  5037.3 1608.95  5040.9 1610.23  5054.0 1611.61  5063.5 1612.30  5076.2 1612.06
  5084.7 1612.55  5090.6 1613.23  5096.7 1614.81  5106.0 1617.68  5127.2 1618.18
  5142.6 1619.25  5153.9 1619.28  5215.8 1620.29  5279.5 1620.50  5459.8 1624.25
#Mann=6,-1,0
  4673.9    0.07       0  4979.6   0.035       0  4997.5   0.035       0
  5037.3   0.035       0  5096.7    0.07       0  5153.9   0.035       0
Bank Sta=4997.5,5037.3
Exp/Cntr=0.3,0.1

Type RM Length L Ch R = 1,25112,365,365,365
BEGIN DESCRIPTION:
Mapping XS 55eb3d9e
END DESCRIPTION:
XS GIS Cut Line= 3
      1637452.24      6952797.19      1637801.18      6952935.21
      1638208.50      6953103.08
#Sta/Elev= 30
  4624.4 1629.45  4631.1 1629.46  4744.6 1628.76  4833.8 1626.65  4874.7 1624.64
  4887.9 1623.17  4899.0 1619.20  4912.2 1615.33  4917.7 1613.03  4936.6 1608.80
  4960.7 1608.96  4962.3 1607.00  4963.3 1606.50  5001.1 1606.50  5002.1 1607.00
  5004.4 1607.78  5014.6 1607.96  5036.2 1611.35  5057.9 1612.95  5067.9 1612.58
  5090.3 1613.69  5097.3 1613.00  5111.9 1613.45  5121.2 1612.73  5133.6 1613.22
  5144.4 1614.76  5150.6 1617.15  5174.5 1618.90  5286.5 1620.48  5440.2 1624.14
#Mann=5,-1,0
  4624.4   0.035       0  4631.1    0.07       0  4899.0   0.035       0
  4962.3   0.035       0  5002.1   0.035       0
Bank Sta=4962.3,5002.1
Exp/Cntr=0.3,0.1

Type RM Length L Ch R = 1,24747,406,406,406
BEGIN DESCRIPTION:
Mapping XS c7efbef1
END DESCRIPTION:
XS GIS Cut Line= 3
      1637377.84      6953203.43      1637752.87      6953284.16
      1638209.94      6953389.64
#Sta/Elev= 30
  4617.2 1627.66  4655.2 1627.76  4666.6 1627.25  4798.4 1625.93  4804.4 1625.25
  4853.7 1623.64  4870.0 1622.28  4880.4 1619.99  4890.5 1617.40  4897.9 1613.99
  4903.0 1613.64  4910.9 1611.71  4931.4 1608.52  4952.4 1607.06  4962.1 1604.99
  4991.5 1605.54  4993.4 1604.21  4994.4 1603.71  5032.2 1603.71  5033.2 1604.21
  5033.8 1608.95  5039.5 1611.58  5054.3 1613.22  5082.3 1615.28  5136.4 1617.17
  5228.8 1618.85  5258.5 1621.66  5306.4 1623.46  5422.8 1624.36  5469.9 1625.07
#Mann=5,-1,0
  4617.2    0.07       0  4880.4   0.035       0  4993.4   0.035       0
  5033.2   0.035       0  5422.8    0.07       0
Bank Sta=4993.4,5033.2
Exp/Cntr=0.3,0.1

Type RM Length L Ch R = 1,24341,333,333,333
BEGIN DESCRIPTION:
Mapping XS 61ea7349
END DESCRIPTION:
XS GIS Cut Line= 3
      1637314.09      6953525.06      1637704.70      6953674.79
      1638130.89      6953829.41
#Sta/Elev= 30
  4582.2 1626.23  4711.2 1625.65  4832.4 1623.71  4848.4 1621.83  4850.7 1621.52
  4856.1 1621.86  4880.7 1613.29  4886.1 1612.87  4893.8 1611.16  4910.8 1609.38
  4925.9 1609.59  4940.8 1607.74  4947.3 1605.47  4958.0 1603.27  4970.8 1603.53
  4978.1 1602.01  4979.1 1601.51  5017.0 1601.51  5018.0 1602.01  5020.7 1604.58
  5026.0 1605.90  5032.8 1611.14  5043.4 1614.80  5051.3 1615.38  5117.9 1616.89
  5160.4 1616.94  5266.8 1618.86  5352.2 1619.86  5426.4 1623.08  5453.9 1625.30
#Mann=5,-1,0
  4582.2   0.035       0  4832.4    0.07       0  4848.4   0.035       0
  4978.1   0.035       0  5018.0   0.035       0
Bank Sta=4978.1,5018
Exp/Cntr=0.3,0.1

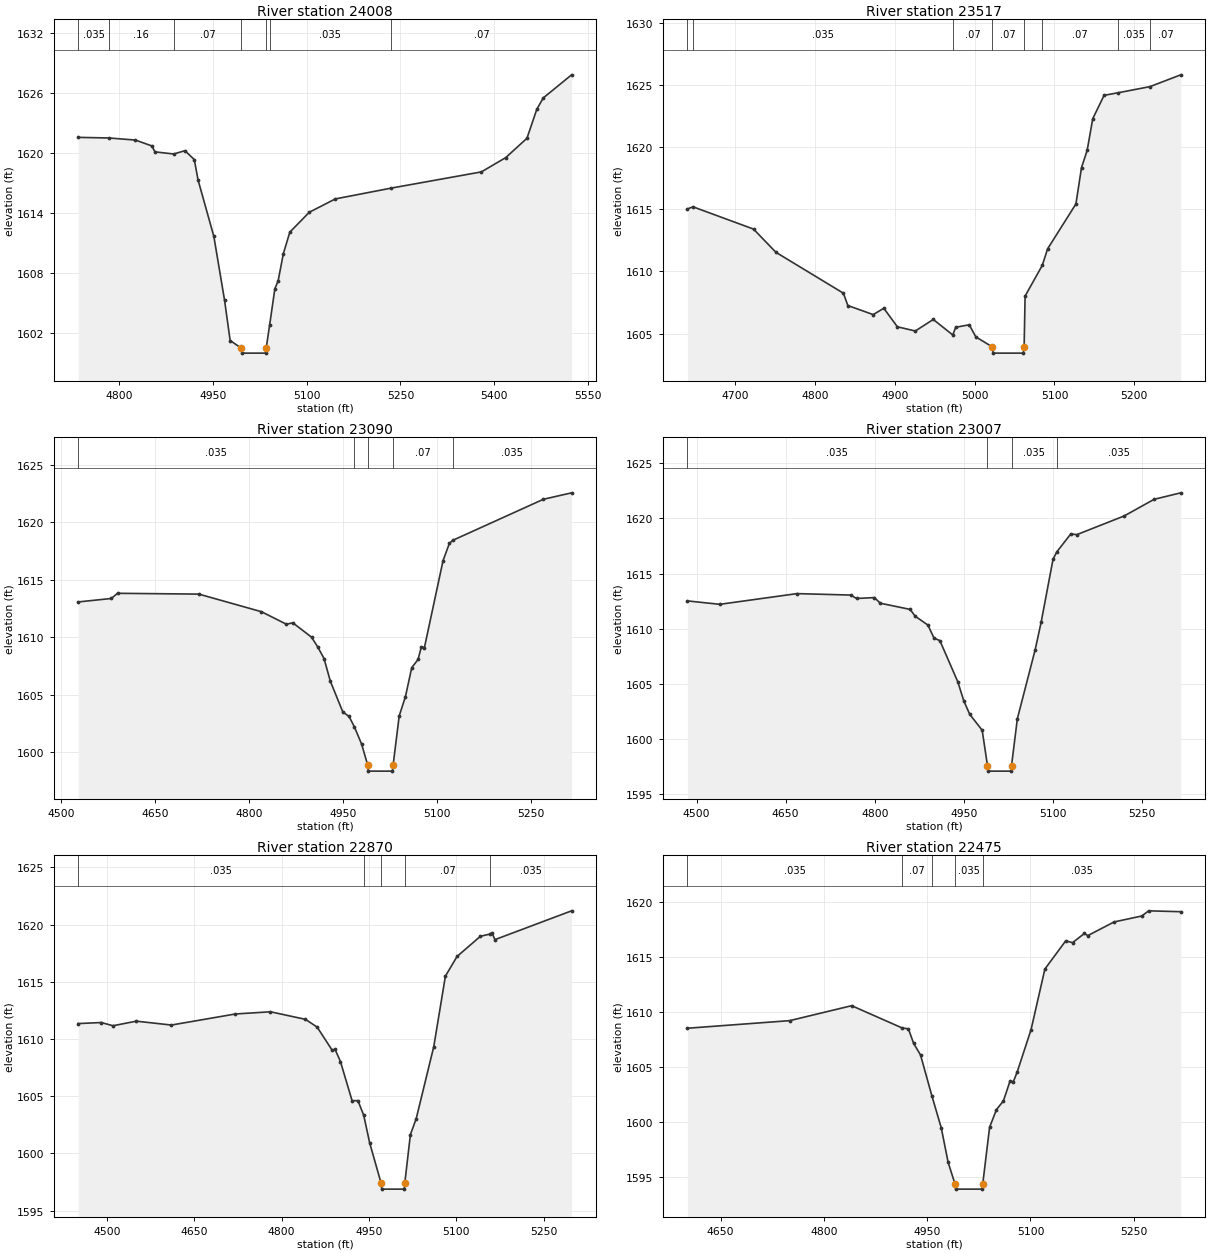
Type RM Length L Ch R = 1,24008,491,491,491
BEGIN DESCRIPTION:
Mapping XS e5532511
END DESCRIPTION:
XS GIS Cut Line= 3
      1637353.34      6953873.50      1637603.31      6953958.56
      1638108.51      6954102.65
#Sta/Elev= 30
  4734.5 1621.59  4783.7 1621.53  4826.1 1621.32  4852.1 1620.74  4857.4 1620.14
  4887.3 1619.93  4905.3 1620.26  4920.2 1619.37  4926.4 1617.30  4951.5 1611.70
  4968.6 1605.34  4977.6 1601.29  4995.4 1600.53  4996.4 1600.03  5034.3 1600.03
  5035.3 1600.53  5040.7 1602.80  5049.2 1606.48  5054.4 1607.25  5062.7 1609.96
  5073.1 1612.12  5104.3 1614.11  5145.9 1615.44  5235.3 1616.52  5379.6 1618.14
  5418.6 1619.57  5452.5 1621.50  5468.3 1624.40  5478.6 1625.53  5523.9 1627.84
#Mann=7,-1,0
  4734.5   0.035       0  4783.7    0.16       0  4887.3    0.07       0
  4995.4    0.07       0  5035.3    0.07       0  5040.7   0.035       0
  5235.3    0.07       0
Bank Sta=4995.4,5035.3
Exp/Cntr=0.3,0.1

Type RM Length L Ch R = 1,23517,427,427,427
BEGIN DESCRIPTION:
Mapping XS ebd70ad8
END DESCRIPTION:
XS GIS Cut Line= 3
      1637363.50      6954098.72      1637522.36      6954424.27
      1637705.43      6954603.44
#Sta/Elev= 30
  4639.9 1615.03  4647.0 1615.20  4722.8 1613.41  4750.9 1611.54  4835.5 1608.25
  4841.0 1607.26  4872.8 1606.53  4886.1 1607.04  4903.1 1605.55  4925.6 1605.21
  4948.1 1606.14  4972.6 1604.89  4976.2 1605.51  4993.2 1605.71  5001.4 1604.74
  5022.1 1603.93  5023.1 1603.43  5061.0 1603.43  5062.0 1603.93  5063.2 1608.02
  5084.8 1610.50  5091.4 1611.82  5126.9 1615.43  5133.9 1618.35  5141.0 1619.74
  5148.0 1622.29  5162.2 1624.17  5179.2 1624.37  5219.7 1624.87  5258.3 1625.82
#Mann=8,-1,0
  4639.9    0.16       0  4647.0   0.035       0  4972.6    0.07       0
  5022.1    0.07       0  5062.0    0.07       0  5084.8    0.07       0
  5179.2   0.035       0  5219.7    0.07       0
Bank Sta=5022.1,5062
Exp/Cntr=0.3,0.1

Type RM Length L Ch R = 1,23090,83,83,83
BEGIN DESCRIPTION:
Mapping XS 512d3c43
END DESCRIPTION:
XS GIS Cut Line= 3
      1637138.35      6954065.17      1637135.74      6954540.47
      1637153.97      6954852.93
#Sta/Elev= 30
  4526.9 1613.06  4579.7 1613.36  4589.7 1613.81  4719.7 1613.74  4819.7 1612.21
  4859.7 1611.12  4869.7 1611.25  4899.7 1610.00  4909.7 1609.14  4919.7 1608.14
  4929.7 1606.18  4949.7 1603.50  4959.7 1603.11  4968.3 1602.19  4979.7 1600.71
  4989.6 1598.86  4990.6 1598.36  5029.0 1598.36  5030.0 1598.86  5039.8 1603.16
  5049.8 1604.84  5059.8 1607.35  5069.9 1608.06  5075.1 1609.15  5080.1 1609.10
  5109.9 1616.66  5119.9 1618.14  5125.2 1618.41  5270.2 1621.98  5315.2 1622.54
#Mann=5,-1,0
  4526.9   0.035       0  4968.3    0.07       0  4989.6    0.07       0
  5030.0    0.07       0  5125.2   0.035       0
Bank Sta=4989.6,5030
Exp/Cntr=0.3,0.1

Type RM Length L Ch R = 1,23007,137,137,137
BEGIN DESCRIPTION:
Mapping XS 43da001d
END DESCRIPTION:
XS GIS Cut Line= 4
      1637058.92      6954023.56      1637040.69      6954410.26
      1637052.41      6954541.77      1637058.92      6954852.94
#Sta/Elev= 30
  4484.6 1612.53  4539.1 1612.22  4669.1 1613.19  4759.3 1613.06  4769.4 1612.75
  4799.4 1612.83  4809.4 1612.32  4859.5 1611.76  4868.1 1611.14  4889.5 1610.34
  4899.6 1609.17  4909.6 1608.93  4939.7 1605.21  4949.8 1603.48  4959.8 1602.26
  4980.8 1600.81  4989.7 1597.61  4990.7 1597.11  5029.2 1597.11  5030.2 1597.61
  5040.0 1601.86  5070.0 1608.11  5080.0 1610.59  5100.0 1616.29  5106.2 1616.96
  5130.0 1618.60  5140.0 1618.53  5220.0 1620.23  5270.1 1621.73  5315.0 1622.32
#Mann=4,-1,0
  4484.6   0.035       0  4989.7    0.07       0  5030.2   0.035       0
  5106.2   0.035       0
Bank Sta=4989.7,5030.2
Exp/Cntr=0.3,0.1

Type RM Length L Ch R = 1,22870,395,395,395
BEGIN DESCRIPTION:
Mapping XS 38dbeecf
END DESCRIPTION:
XS GIS Cut Line= 3
      1636888.34      6953988.34      1636915.69      6954539.17
      1636923.46      6954834.56
#Sta/Elev= 30
  4450.9 1611.35  4490.6 1611.44  4510.6 1611.16  4550.7 1611.56  4610.8 1611.22
  4720.9 1612.19  4781.0 1612.38  4841.0 1611.72  4861.1 1611.04  4886.9 1609.02
  4891.9 1609.09  4901.1 1608.03  4921.1 1604.60  4931.1 1604.61  4941.0 1603.34
  4951.2 1600.93  4971.0 1597.37  4972.0 1596.87  5010.5 1596.87  5011.5 1597.37
  5021.2 1601.64  5031.2 1603.04  5061.3 1609.33  5081.3 1615.50  5101.3 1617.22
  5141.3 1618.98  5157.8 1619.18  5161.3 1619.27  5166.3 1618.69  5297.9 1621.21
#Mann=5,-1,0
  4450.9   0.035       0  4941.0    0.07       0  4971.0    0.07       0
  5011.5    0.07       0  5157.8   0.035       0
Bank Sta=4971,5011.5
Exp/Cntr=0.3,0.1

Type RM Length L Ch R = 1,22475,486,486,486
BEGIN DESCRIPTION:
Mapping XS 37ea3657
END DESCRIPTION:
XS GIS Cut Line= 3
      1636537.61      6954039.61      1636553.23      6954440.69
      1636583.05      6954754.39
#Sta/Elev= 30
  4601.7 1608.50  4750.2 1609.19  4840.3 1610.55  4913.8 1608.52  4922.7 1608.45
  4930.3 1607.12  4940.3 1606.07  4956.9 1602.33  4970.4 1599.45  4980.4 1596.31
  4990.2 1594.38  4991.2 1593.88  5029.7 1593.88  5030.7 1594.38  5040.6 1599.50
  5050.6 1601.11  5060.7 1601.90  5070.1 1603.67  5075.2 1603.66  5080.7 1604.53
  5100.8 1608.37  5120.9 1613.88  5151.1 1616.44  5161.1 1616.28  5178.2 1617.11
  5183.3 1616.92  5221.4 1618.16  5261.6 1618.70  5271.6 1619.17  5318.2 1619.09
#Mann=5,-1,0
  4601.7   0.035       0  4913.8    0.07       0  4956.9   0.035       0
  4990.2   0.035       0  5030.7   0.035       0
Bank Sta=4990.2,5030.7
Exp/Cntr=0.3,0.1

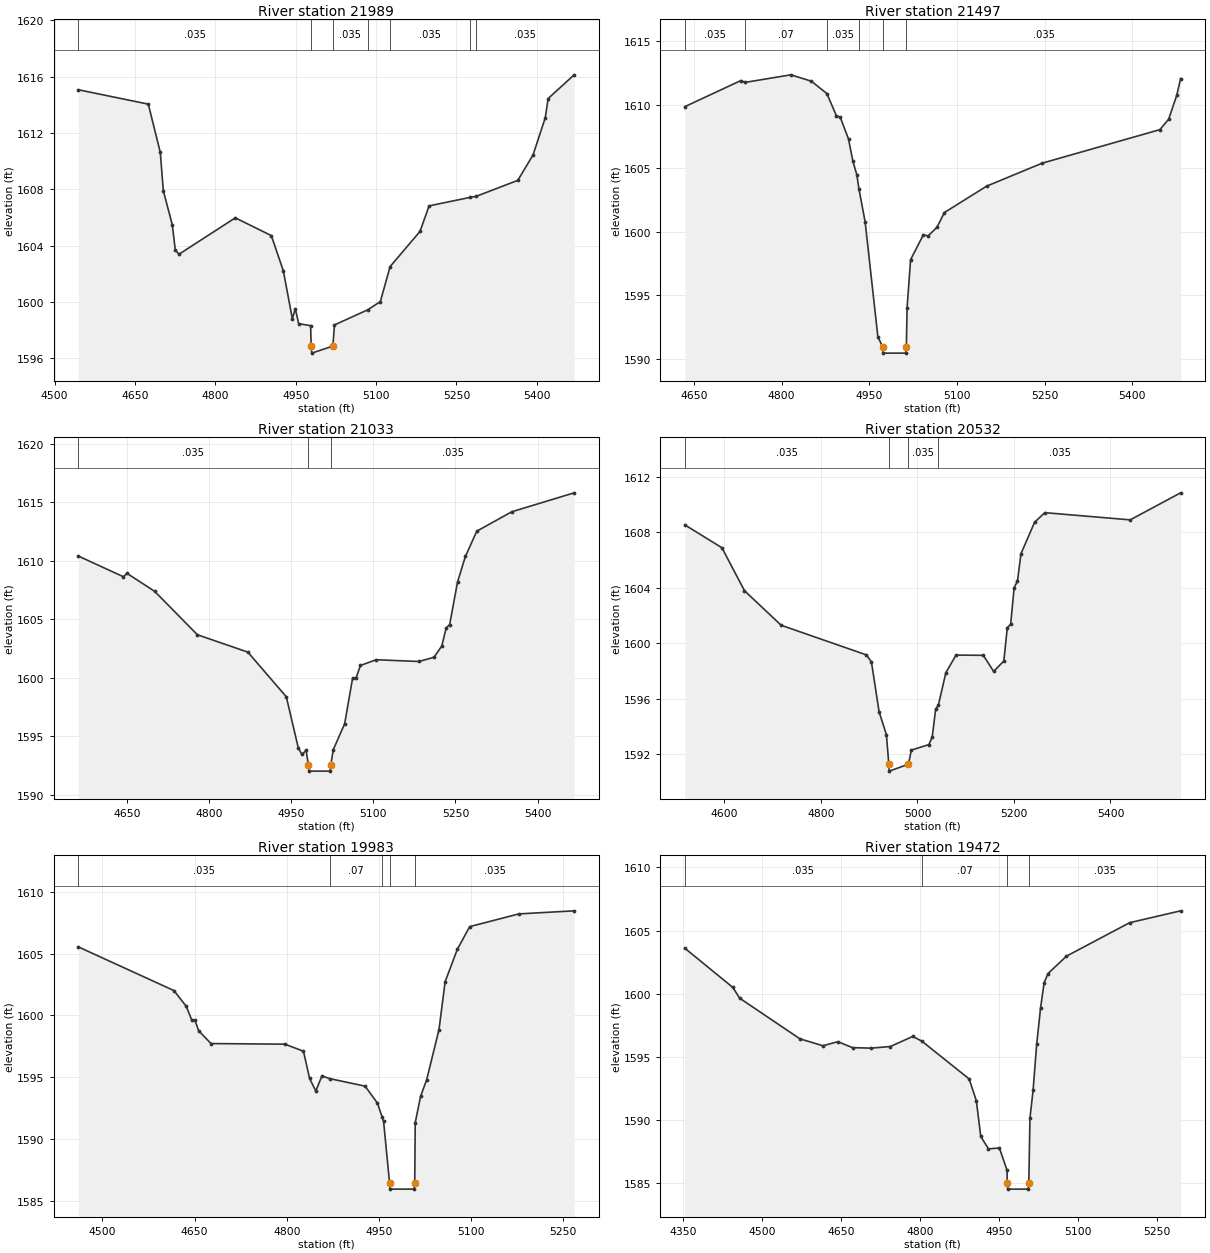
Type RM Length L Ch R = 1,21989,492,492,492
BEGIN DESCRIPTION:
Mapping XS 03ff68cc
END DESCRIPTION:
XS GIS Cut Line= 3
      1635880.06      6953979.76      1636084.48      6954391.21
      1636282.39      6954813.06
#Sta/Elev= 30
  4544.4 1615.07  4675.0 1614.05  4697.4 1610.62  4703.0 1607.91  4719.8 1605.48
  4725.4 1603.69  4732.3 1603.40  4837.4 1605.98  4904.6 1604.72  4927.0 1602.22
  4943.8 1598.83  4949.4 1599.53  4955.6 1598.47  4977.9 1598.33  4979.0 1596.88
  4980.0 1596.38  5019.5 1596.88  5022.4 1598.38  5084.9 1599.46  5108.1 1600.04
  5126.3 1602.52  5182.1 1605.02  5199.1 1606.83  5275.2 1607.43  5287.2 1607.51
  5364.6 1608.64  5393.0 1610.44  5415.8 1613.07  5421.3 1614.45  5469.8 1616.13
#Mann=7,-1,0
  4544.4   0.035       0  4979.0   0.035       0  5019.5   0.035       0
  5084.9    0.07       0  5126.3   0.035       0  5275.2    0.07       0
  5287.2   0.035       0
Bank Sta=4979,5019.5
Exp/Cntr=0.3,0.1

Type RM Length L Ch R = 1,21497,464,464,464
BEGIN DESCRIPTION:
Mapping XS 9cf2444d
END DESCRIPTION:
XS GIS Cut Line= 3
      1635457.83      6954369.48      1635702.65      6954645.55
      1636100.52      6954912.10
#Sta/Elev= 30
  4634.6 1609.85  4730.6 1611.91  4737.3 1611.76  4815.9 1612.36  4851.0 1611.86
  4877.6 1610.88  4893.7 1609.15  4900.4 1609.02  4914.6 1607.30  4922.1 1605.54
  4928.8 1604.49  4932.3 1603.39  4943.0 1600.77  4964.8 1591.71  4972.9 1590.93
  4973.9 1590.43  5012.5 1590.43  5013.5 1590.93  5014.7 1593.98  5020.7 1597.79
  5042.5 1599.75  5050.7 1599.67  5065.7 1600.34  5078.6 1601.51  5150.9 1603.59
  5245.8 1605.40  5447.0 1608.04  5462.0 1608.86  5475.9 1610.75  5482.5 1612.07
#Mann=6,-1,0
  4634.6   0.035       0  4737.3    0.07       0  4877.6   0.035       0
  4932.3    0.07       0  4972.9   0.035       0  5013.5   0.035       0
Bank Sta=4972.9,5013.5
Exp/Cntr=0.3,0.1

Type RM Length L Ch R = 1,21033,501,501,501
BEGIN DESCRIPTION:
Mapping XS 2444017e
END DESCRIPTION:
XS GIS Cut Line= 3
      1635016.67      6954510.14      1635303.13      6954848.67
      1635593.91      6955208.89
#Sta/Elev= 30
  4560.6 1610.41  4643.0 1608.64  4649.6 1608.93  4700.2 1607.39  4778.2 1603.68
  4870.5 1602.19  4940.8 1598.37  4962.8 1593.98  4969.3 1593.44  4977.0 1593.78
  4981.3 1592.51  4982.3 1592.01  5021.0 1592.01  5022.0 1592.51  5026.7 1593.85
  5047.5 1596.07  5061.9 1599.95  5068.3 1599.98  5076.3 1601.05  5105.1 1601.54
  5183.1 1601.39  5210.7 1601.75  5225.0 1602.71  5233.0 1604.25  5239.4 1604.55
  5253.8 1608.19  5268.2 1610.38  5289.0 1612.54  5353.0 1614.20  5467.0 1615.82
#Mann=3,-1,0
  4560.6   0.035       0  4981.3   0.035       0  5022.0   0.035       0
Bank Sta=4981.3,5022
Exp/Cntr=0.3,0.1

Type RM Length L Ch R = 1,20532,549,549,549
BEGIN DESCRIPTION:
Mapping XS b086ce77
END DESCRIPTION:
XS GIS Cut Line= 3
      1634738.90      6954563.56      1634860.42      6955032.27
      1635238.02      6955422.89
#Sta/Elev= 30
  4517.9 1608.53  4594.8 1606.88  4641.6 1603.78  4717.6 1601.29  4894.4 1599.15
  4904.7 1598.64  4920.5 1595.05  4935.7 1593.40  4940.7 1591.27  4941.7 1590.77
  4981.4 1591.27  4987.4 1592.29  5023.7 1592.68  5030.6 1593.22  5037.8 1595.25
  5043.3 1595.52  5058.9 1597.87  5080.0 1599.14  5136.6 1599.12  5157.9 1597.96
  5179.0 1598.71  5186.2 1601.11  5193.2 1601.37  5200.4 1604.00  5207.3 1604.47
  5214.5 1606.44  5242.8 1608.72  5263.9 1609.41  5440.9 1608.89  5545.4 1610.84
#Mann=4,-1,0
  4517.9   0.035       0  4940.7    0.07       0  4981.4   0.035       0
  5043.3   0.035       0
Bank Sta=4940.7,4981.4
Exp/Cntr=0.3,0.1

Type RM Length L Ch R = 1,19983,511,511,511
BEGIN DESCRIPTION:
Mapping XS 63bee427
END DESCRIPTION:
XS GIS Cut Line= 3
      1634407.29      6954642.95      1634357.38      6955185.48
      1634359.55      6955448.05
#Sta/Elev= 30
  4460.7 1605.55  4616.4 1602.01  4636.5 1600.73  4645.5 1599.61  4650.5 1599.62
  4656.6 1598.76  4676.7 1597.72  4797.2 1597.67  4827.3 1597.10  4837.3 1594.89
  4847.4 1593.88  4857.4 1595.10  4870.1 1594.88  4927.7 1594.27  4947.8 1592.89
  4955.5 1591.75  4957.8 1591.41  4967.5 1586.43  4968.5 1585.93  5007.5 1585.93
  5008.5 1586.43  5009.3 1591.31  5018.0 1593.44  5028.0 1594.80  5048.0 1598.85
  5058.0 1602.73  5078.0 1605.37  5098.0 1607.19  5178.0 1608.22  5268.1 1608.47
#Mann=5,-1,0
  4460.7   0.035       0  4870.1    0.07       0  4955.5   0.035       0
  4967.5   0.035       0  5008.5   0.035       0
Bank Sta=4967.5,5008.5
Exp/Cntr=0.3,0.1

Type RM Length L Ch R = 1,19472,329,329,329
BEGIN DESCRIPTION:
Mapping XS 196de0dd
END DESCRIPTION:
XS GIS Cut Line= 3
      1634248.86      6954614.75      1633858.25      6955137.74
      1633660.75      6955350.42
#Sta/Elev= 30
  4352.5 1603.60  4443.9 1600.49  4456.8 1599.64  4571.4 1596.42  4615.2 1595.87
  4643.6 1596.19  4671.5 1595.72  4706.9 1595.68  4743.5 1595.81  4786.1 1596.61
  4803.5 1596.23  4893.3 1593.24  4907.0 1591.51  4915.4 1588.68  4930.0 1587.70
  4950.8 1587.77  4965.4 1586.00  4965.7 1585.01  4966.7 1584.51  5005.8 1584.51
  5006.8 1585.01  5008.9 1590.12  5014.9 1592.33  5021.7 1595.97  5029.1 1598.86
  5035.9 1600.86  5043.3 1601.59  5078.4 1602.97  5198.6 1605.62  5295.5 1606.56
#Mann=4,-1,0
  4352.5   0.035       0  4803.5    0.07       0  4965.7   0.035       0
  5006.8   0.035       0
Bank Sta=4965.7,5006.8
Exp/Cntr=0.3,0.1

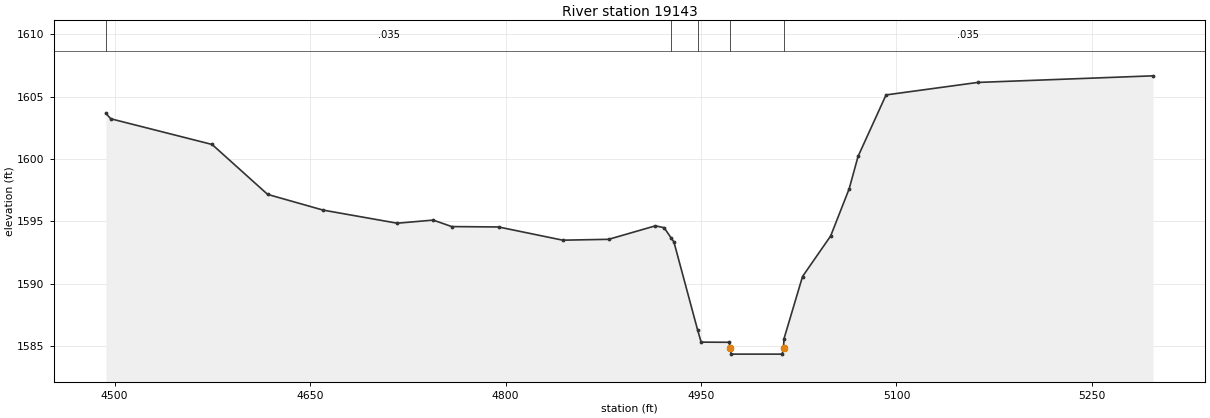
Type RM Length L Ch R = 1,19143,453,453,453
BEGIN DESCRIPTION:
Mapping XS 78dbbabf
END DESCRIPTION:
XS GIS Cut Line= 3
      1634023.17      6954491.04      1633680.30      6954875.15
      1633485.01      6955087.80
#Sta/Elev= 30
  4493.3 1603.66  4497.0 1603.22  4574.8 1601.16  4617.4 1597.16  4660.0 1595.90
  4716.9 1594.85  4744.5 1595.10  4758.7 1594.58  4794.6 1594.55  4843.9 1593.49
  4879.1 1593.56  4915.0 1594.64  4921.7 1594.49  4927.0 1593.68  4929.2 1593.35
  4947.3 1586.33  4950.1 1585.32  4971.8 1585.31  4972.2 1584.86  4973.2 1584.36
  5012.3 1584.36  5013.3 1584.86  5013.7 1585.60  5027.9 1590.58  5049.5 1593.83
  5063.7 1597.61  5070.5 1600.20  5092.0 1605.13  5162.3 1606.13  5296.9 1606.66
#Mann=5,-1,0
  4493.3   0.035       0  4927.0    0.07       0  4947.3   0.035       0
  4972.2   0.035       0  5013.3   0.035       0
Bank Sta=4972.2,5013.3
Exp/Cntr=0.3,0.1