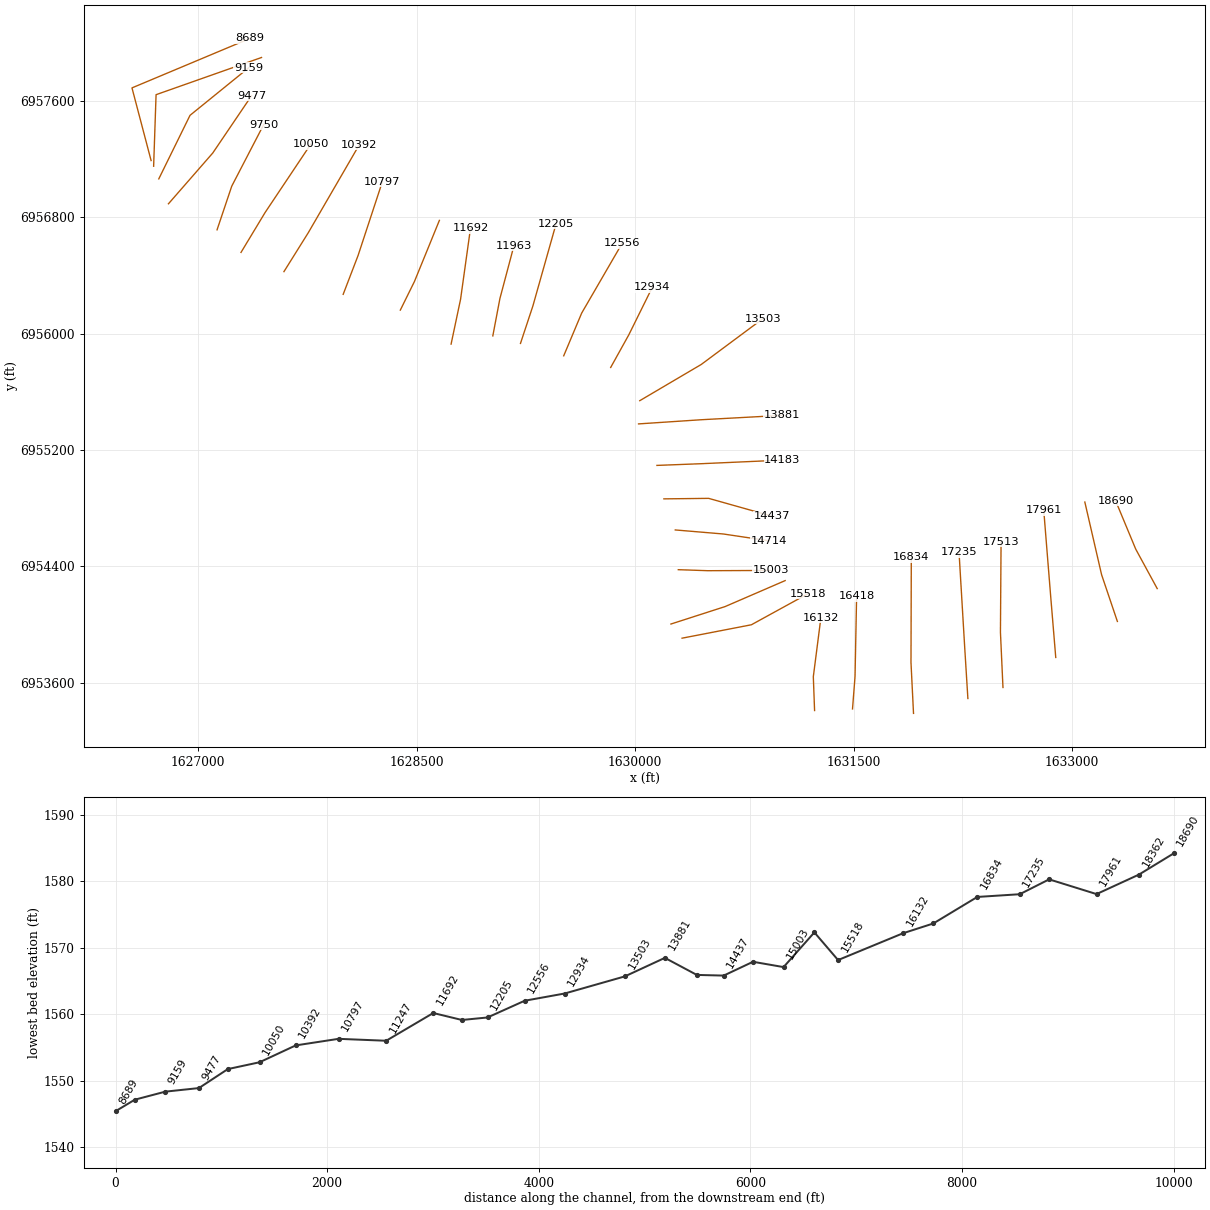
HEC-RAS study Chimney Creek.prj: Chimney Creek Base Level Engineering

--- Chimney Creek.g01 (geometry) --- (continued)

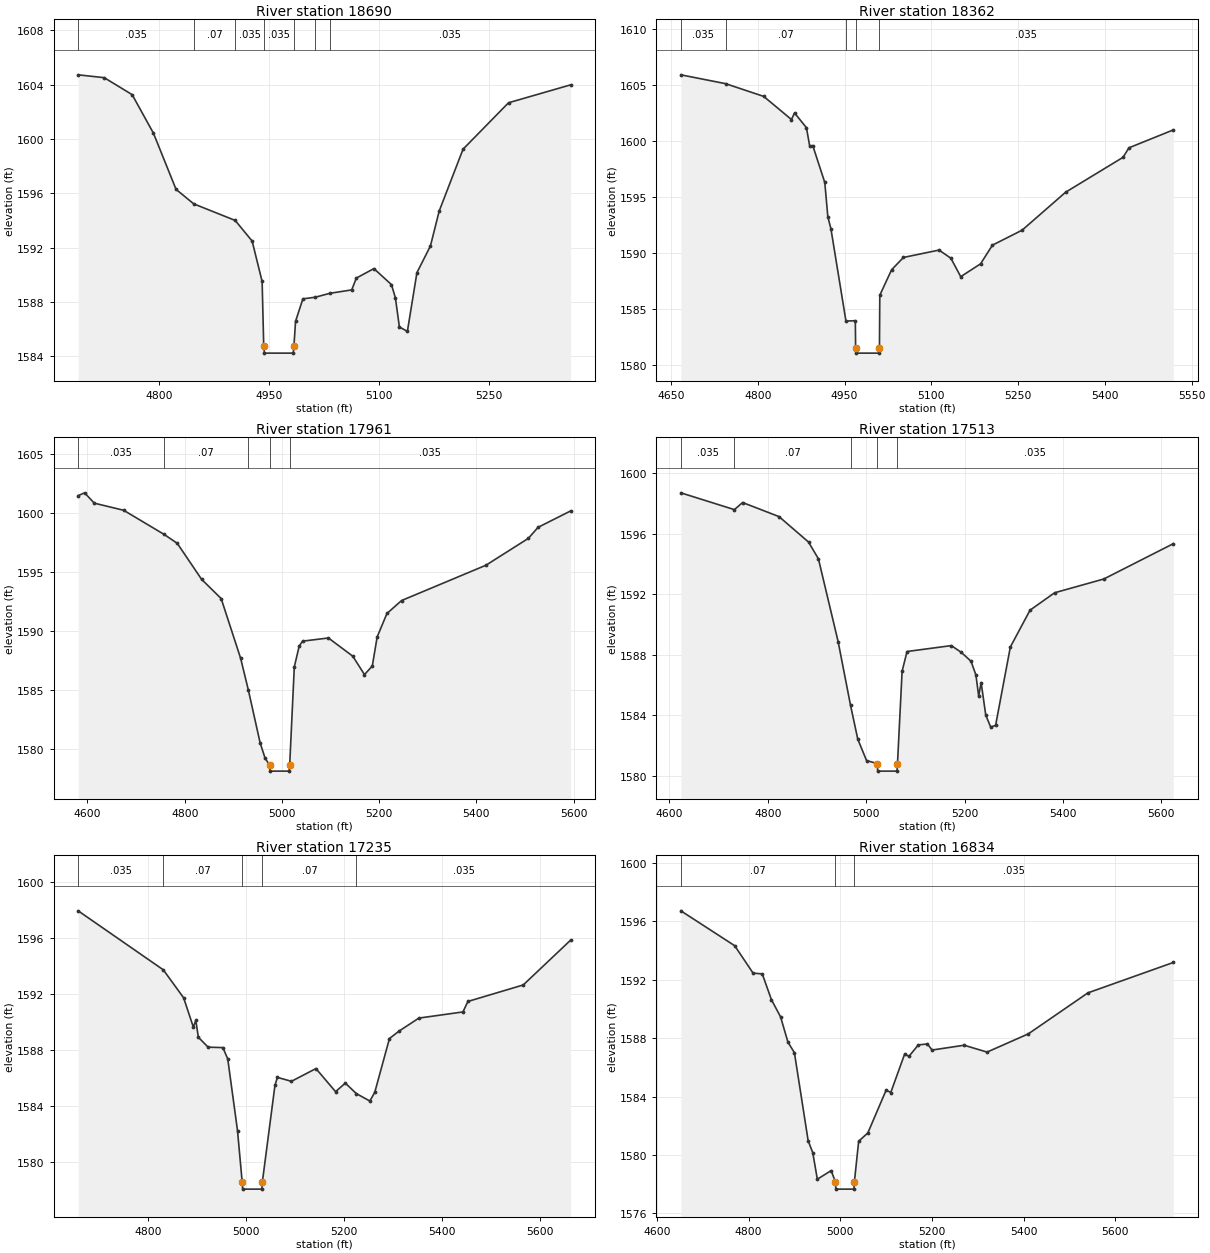
Type RM Length L Ch R = 1,18690,328,328,328
BEGIN DESCRIPTION:
Mapping XS 594204ba
END DESCRIPTION:
XS GIS Cut Line= 3
      1633584.82      6954247.95      1633437.24      6954519.25
      1633298.45      6954853.22
#Sta/Elev= 30
  4690.1 1604.73  4725.6 1604.52  4763.6 1603.27  4792.6 1600.43  4823.4 1596.29
  4847.5 1595.22  4903.9 1594.00  4927.0 1592.48  4940.6 1589.50  4942.8 1584.72
  4943.8 1584.22  4982.9 1584.22  4983.9 1584.72  4986.1 1586.56  4996.1 1588.22
  5013.0 1588.34  5033.0 1588.63  5062.6 1588.88  5068.9 1589.75  5092.8 1590.45
  5116.7 1589.27  5122.1 1588.29  5127.5 1586.15  5138.4 1585.82  5151.4 1590.15
  5169.8 1592.12  5181.7 1594.69  5214.2 1599.25  5276.1 1602.67  5360.6 1603.99
#Mann=7,-1,0
  4690.1   0.035       0  4847.5    0.07       0  4903.9   0.035       0
  4942.8   0.035       0  4983.9   0.035       0  5013.0    0.07       0
  5033.0   0.035       0
Bank Sta=4942.8,4983.9
Exp/Cntr=0.3,0.1

Type RM Length L Ch R = 1,18362,401,401,401
BEGIN DESCRIPTION:
Mapping XS 2195eb67
END DESCRIPTION:
XS GIS Cut Line= 3
      1633311.36      6954022.31      1633202.86      6954343.47
      1633087.85      6954842.60
#Sta/Elev= 30
  4667.0 1605.93  4744.3 1605.14  4810.2 1604.00  4858.2 1601.93  4863.5 1602.52
  4884.1 1601.20  4889.7 1599.56  4895.0 1599.60  4915.8 1596.30  4921.1 1593.22
  4926.4 1592.16  4952.4 1583.90  4968.6 1583.93  4969.1 1581.53  4970.1 1581.03
  5009.3 1581.03  5010.3 1581.53  5010.9 1586.21  5031.2 1588.48  5051.7 1589.59
  5113.3 1590.25  5133.8 1589.52  5150.8 1587.87  5185.1 1589.02  5205.6 1590.69
  5256.9 1592.03  5332.2 1595.43  5431.4 1598.55  5441.6 1599.40  5518.2 1601.00
#Mann=5,-1,0
  4667.0   0.035       0  4744.3    0.07       0  4952.4   0.035       0
  4969.1   0.035       0  5010.3   0.035       0
Bank Sta=4969.1,5010.3
Exp/Cntr=0.3,0.1

Type RM Length L Ch R = 1,17961,448,448,448
BEGIN DESCRIPTION:
Mapping XS dd7f3e67
END DESCRIPTION:
XS GIS Cut Line= 3
      1632888.20      6953774.84      1632853.47      6954193.73
      1632805.86      6954784.59
#Sta/Elev= 30
  4580.8 1601.49  4594.0 1601.73  4614.1 1600.85  4674.3 1600.25  4757.6 1598.20
  4784.7 1597.44  4834.8 1594.38  4875.0 1592.75  4915.1 1587.67  4930.9 1584.99
  4955.2 1580.49  4965.3 1579.20  4974.8 1578.59  4975.8 1578.09  5015.0 1578.09
  5016.0 1578.59  5025.5 1586.94  5035.5 1588.70  5042.4 1589.13  5095.7 1589.40
  5145.9 1587.85  5169.9 1586.29  5186.0 1587.02  5196.0 1589.49  5216.1 1591.48
  5246.2 1592.58  5419.8 1595.58  5507.0 1597.86  5527.1 1598.80  5593.9 1600.19
#Mann=5,-1,0
  4580.8   0.035       0  4757.6    0.07       0  4930.9   0.035       0
  4974.8   0.035       0  5016.0   0.035       0
Bank Sta=4974.8,5016
Exp/Cntr=0.3,0.1

Type RM Length L Ch R = 1,17513,278,278,278
BEGIN DESCRIPTION:
Mapping XS 65033828
END DESCRIPTION:
XS GIS Cut Line= 3
      1632525.78      6953568.74      1632508.42      6953948.50
      1632512.76      6954569.13
#Sta/Elev= 30
  4623.4 1598.69  4732.2 1597.58  4748.9 1598.05  4822.9 1597.12  4882.9 1595.44
  4903.0 1594.33  4943.0 1588.87  4968.3 1584.65  4983.0 1582.42  5000.8 1581.01
  5022.5 1580.81  5023.5 1580.31  5062.7 1580.31  5063.7 1580.81  5073.1 1586.91
  5083.1 1588.21  5173.1 1588.60  5193.1 1588.16  5213.1 1587.57  5223.1 1586.66
  5228.7 1585.27  5233.7 1586.16  5243.1 1584.01  5253.1 1583.22  5263.1 1583.33
  5293.1 1588.51  5333.1 1590.94  5383.1 1592.09  5483.1 1593.00  5624.2 1595.33
#Mann=5,-1,0
  4623.4   0.035       0  4732.2    0.07       0  4968.3   0.035       0
  5022.5   0.035       0  5063.7   0.035       0
Bank Sta=5022.5,5063.7
Exp/Cntr=0.3,0.1

Type RM Length L Ch R = 1,17235,401,401,401
BEGIN DESCRIPTION:
Mapping XS 62b5e8e0
END DESCRIPTION:
XS GIS Cut Line= 3
      1632284.89      6953492.81      1632263.19      6953842.16
      1632224.13      6954497.58
#Sta/Elev= 30
  4656.3 1597.97  4830.4 1593.75  4871.9 1591.75  4891.7 1589.66  4896.8 1590.13
  4902.0 1588.93  4922.0 1588.22  4952.1 1588.19  4962.1 1587.38  4982.1 1582.24
  4991.6 1578.57  4992.6 1578.07  5031.8 1578.07  5032.8 1578.57  5058.6 1585.49
  5063.6 1586.06  5092.3 1585.78  5142.4 1586.69  5182.5 1585.04  5202.5 1585.65
  5225.0 1584.90  5252.6 1584.37  5262.6 1584.99  5292.7 1588.84  5312.7 1589.38
  5352.8 1590.30  5442.9 1590.74  5453.0 1591.49  5566.2 1592.67  5662.9 1595.87
#Mann=5,-1,0
  4656.3   0.035       0  4830.4    0.07       0  4991.6    0.07       0
  5032.8    0.07       0  5225.0   0.035       0
Bank Sta=4991.6,5032.8
Exp/Cntr=0.3,0.1

Type RM Length L Ch R = 1,16834,416,416,416
BEGIN DESCRIPTION:
Mapping XS bc5c766d
END DESCRIPTION:
XS GIS Cut Line= 3
      1631911.63      6953390.74      1631894.27      6953740.17
      1631896.44      6954464.00
#Sta/Elev= 30
  4652.5 1596.73  4769.9 1594.34  4810.0 1592.46  4830.0 1592.41  4850.0 1590.64
  4870.0 1589.46  4886.0 1587.73  4900.1 1587.01  4930.1 1580.97  4940.1 1580.16
  4950.1 1578.34  4980.2 1578.93  4989.5 1578.16  4990.5 1577.66  5029.9 1577.66
  5030.9 1578.16  5040.2 1580.94  5060.2 1581.51  5100.2 1584.45  5110.2 1584.28
  5140.2 1586.89  5150.2 1586.77  5170.2 1587.54  5190.2 1587.61  5200.2 1587.19
  5270.2 1587.52  5320.2 1587.05  5410.2 1588.30  5540.2 1591.11  5726.2 1593.19
#Mann=3,-1,0
  4652.5    0.07       0  4989.5    0.07       0  5030.9   0.035       0
Bank Sta=4989.5,5030.9
Exp/Cntr=0.3,0.1

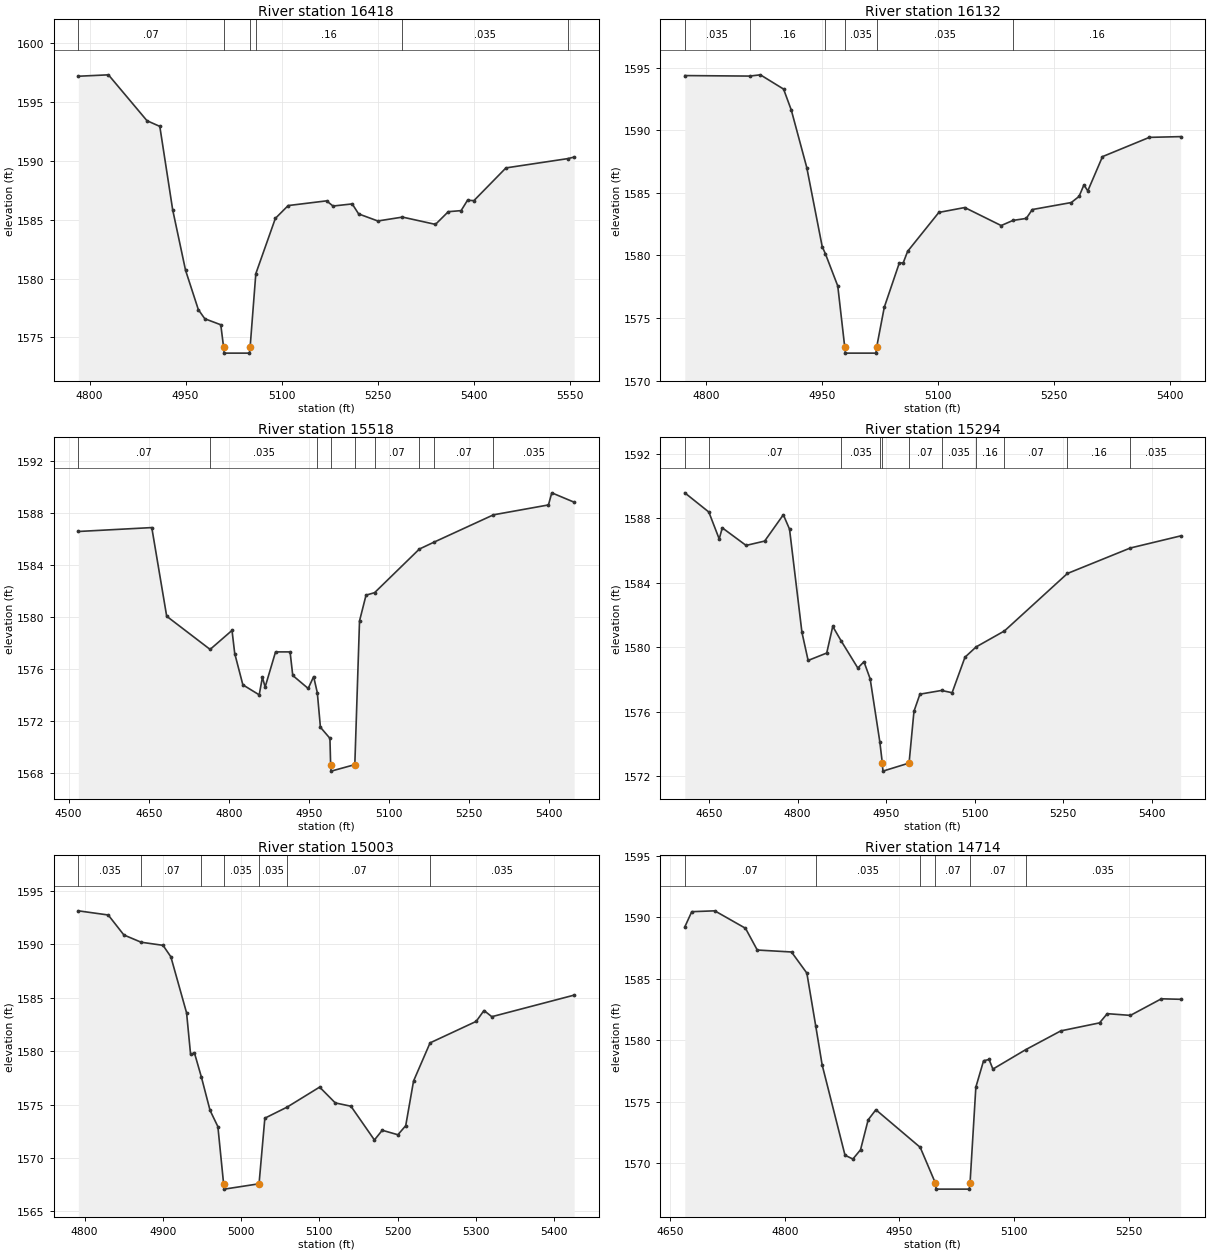
Type RM Length L Ch R = 1,16418,286,286,286
BEGIN DESCRIPTION:
Mapping XS 1ddf9642
END DESCRIPTION:
XS GIS Cut Line= 3
      1631492.79      6953421.14      1631510.16      6953644.68
      1631520.98      6954194.46
#Sta/Elev= 30
  4782.5 1597.19  4829.5 1597.31  4889.7 1593.41  4909.7 1592.93  4929.8 1585.84
  4949.9 1580.70  4969.9 1577.35  4980.0 1576.58  5004.9 1576.07  5009.3 1574.16
  5010.3 1573.66  5049.7 1573.66  5050.7 1574.16  5059.6 1580.41  5090.1 1585.11
  5110.1 1586.20  5170.1 1586.60  5180.1 1586.16  5210.1 1586.34  5220.1 1585.49
  5250.1 1584.89  5288.6 1585.22  5340.1 1584.60  5360.1 1585.68  5380.1 1585.77
  5390.1 1586.65  5400.1 1586.62  5450.1 1589.40  5546.7 1590.19  5556.6 1590.32
#Mann=6,-1,0
  4782.5    0.07       0  5009.3    0.07       0  5050.7    0.07       0
  5059.6    0.16       0  5288.6   0.035       0  5546.7    0.16       0
Bank Sta=5009.3,5050.7
Exp/Cntr=0.3,0.1

Type RM Length L Ch R = 1,16132,614,614,614
BEGIN DESCRIPTION:
Mapping XS c9a489fb
END DESCRIPTION:
XS GIS Cut Line= 3
      1631232.38      6953410.29      1631223.70      6953642.51
      1631275.78      6954048.30
#Sta/Elev= 30
  4772.4 1594.38  4856.3 1594.34  4870.2 1594.44  4900.2 1593.30  4910.2 1591.62
  4930.2 1587.03  4950.2 1580.70  4954.2 1580.15  4970.3 1577.56  4979.3 1572.69
  4980.3 1572.19  5019.7 1572.19  5020.7 1572.69  5030.5 1575.86  5049.9 1579.39
  5055.0 1579.41  5060.7 1580.33  5101.1 1583.44  5134.6 1583.83  5181.7 1582.39
  5197.0 1582.80  5214.2 1582.96  5222.0 1583.67  5272.5 1584.23  5282.5 1584.72
  5288.8 1585.64  5293.8 1585.16  5312.8 1587.90  5373.4 1589.44  5413.9 1589.50
#Mann=6,-1,0
  4772.4   0.035       0  4856.3    0.16       0  4954.2   0.035       0
  4979.3   0.035       0  5020.7   0.035       0  5197.0    0.16       0
Bank Sta=4979.3,5020.7
Exp/Cntr=0.3,0.1

Type RM Length L Ch R = 1,15518,224,224,224
BEGIN DESCRIPTION:
Mapping XS f32c6a75
END DESCRIPTION:
XS GIS Cut Line= 3
      1630322.57      6953907.36      1630798.53      6953999.48
      1631187.18      6954212.92
#Sta/Elev= 30
  4518.1 1586.56  4655.6 1586.86  4683.5 1580.05  4764.8 1577.50  4805.8 1578.96
  4810.9 1577.18  4826.1 1574.78  4856.7 1574.01  4862.7 1575.36  4867.8 1574.61
  4887.3 1577.31  4914.5 1577.31  4919.5 1575.50  4948.4 1574.50  4958.6 1575.41
  4965.5 1574.17  4971.3 1571.52  4989.1 1570.67  4990.4 1568.65  4991.4 1568.15
  5035.7 1568.65  5044.5 1579.69  5056.7 1581.67  5072.7 1581.86  5156.5 1585.21
  5183.9 1585.74  5295.2 1587.84  5398.2 1588.60  5404.4 1589.53  5446.3 1588.81
#Mann=9,-1,0
  4518.1    0.07       0  4764.8   0.035       0  4965.5    0.16       0
  4990.4    0.07       0  5035.7    0.16       0  5072.7    0.07       0
  5156.5   0.035       0  5183.9    0.07       0  5295.2   0.035       0
Bank Sta=4990.4,5035.7
Exp/Cntr=0.3,0.1

Type RM Length L Ch R = 1,15294,291,291,291
BEGIN DESCRIPTION:
Mapping XS 40c71882
END DESCRIPTION:
XS GIS Cut Line= 3
      1630246.19      6954004.58      1630617.97      6954124.48
      1631030.28      6954302.92
#Sta/Elev= 30
  4609.0 1589.57  4649.7 1588.38  4667.3 1586.71  4672.5 1587.40  4712.8 1586.31
  4744.3 1586.58  4775.9 1588.21  4786.4 1587.32  4807.4 1580.93  4817.9 1579.18
  4849.4 1579.64  4859.6 1581.29  4873.9 1580.39  4902.1 1578.71  4912.5 1579.10
  4923.0 1578.04  4939.3 1574.15  4943.6 1572.82  4944.6 1572.32  4988.9 1572.82
  4997.2 1576.03  5007.3 1577.09  5043.9 1577.32  5061.8 1577.18  5083.6 1579.38
  5102.5 1580.02  5150.5 1581.01  5257.1 1584.57  5363.7 1586.15  5448.9 1586.90
#Mann=11,-1,0
  4609.0   0.035       0  4649.7    0.07       0  4873.9   0.035       0
  4939.3    0.07       0  4943.6    0.07       0  4988.9    0.07       0
  5043.9   0.035       0  5102.5    0.16       0  5150.5    0.07       0
  5257.1    0.16       0  5363.7   0.035       0
Bank Sta=4943.6,4988.9
Exp/Cntr=0.3,0.1

Type RM Length L Ch R = 1,15003,289,289,289
BEGIN DESCRIPTION:
Mapping XS 58b2fac7
END DESCRIPTION:
XS GIS Cut Line= 3
      1630296.82      6954377.95      1630498.18      6954371.01
      1630930.20      6954372.74
#Sta/Elev= 30
  4792.0 1593.14  4830.2 1592.75  4850.2 1590.88  4872.3 1590.20  4900.2 1589.91
  4910.2 1588.84  4930.3 1583.59  4935.4 1579.72  4940.4 1579.83  4949.3 1577.56
  4960.3 1574.46  4970.3 1572.94  4977.6 1567.59  4978.6 1567.09  5022.9 1567.59
  5030.3 1573.73  5058.8 1574.77  5100.3 1576.64  5120.3 1575.16  5140.3 1574.85
  5170.3 1571.69  5180.3 1572.60  5200.3 1572.18  5210.3 1573.03  5220.3 1577.21
  5241.4 1580.78  5300.3 1582.79  5310.3 1583.81  5320.3 1583.23  5425.5 1585.25
#Mann=7,-1,0
  4792.0   0.035       0  4872.3    0.07       0  4949.3   0.035       0
  4977.6   0.035       0  5022.9   0.035       0  5058.8    0.07       0
  5241.4   0.035       0
Bank Sta=4977.6,5022.9
Exp/Cntr=0.3,0.1

Type RM Length L Ch R = 1,14714,277,277,277
BEGIN DESCRIPTION:
Mapping XS 78a41690
END DESCRIPTION:
XS GIS Cut Line= 3
      1630275.91      6954650.98      1630605.76      6954623.20
      1630919.96      6954576.33
#Sta/Elev= 30
  4669.3 1589.23  4678.4 1590.47  4708.5 1590.54  4748.7 1589.12  4764.1 1587.35
  4808.9 1587.19  4829.0 1585.47  4840.7 1581.13  4849.0 1578.00  4878.9 1570.65
  4889.2 1570.34  4899.2 1571.09  4909.2 1573.53  4919.3 1574.35  4977.3 1571.29
  4997.1 1568.39  4998.1 1567.89  5041.5 1567.89  5042.5 1568.39  5050.1 1576.19
  5060.2 1578.34  5067.4 1578.44  5072.4 1577.66  5115.3 1579.24  5161.3 1580.77
  5211.9 1581.42  5222.0 1582.17  5252.3 1582.03  5292.8 1583.38  5318.0 1583.34
#Mann=6,-1,0
  4669.3    0.07       0  4840.7   0.035       0  4977.3    0.07       0
  4997.1    0.07       0  5042.5    0.07       0  5115.3   0.035       0
Bank Sta=4997.1,5042.5
Exp/Cntr=0.3,0.1

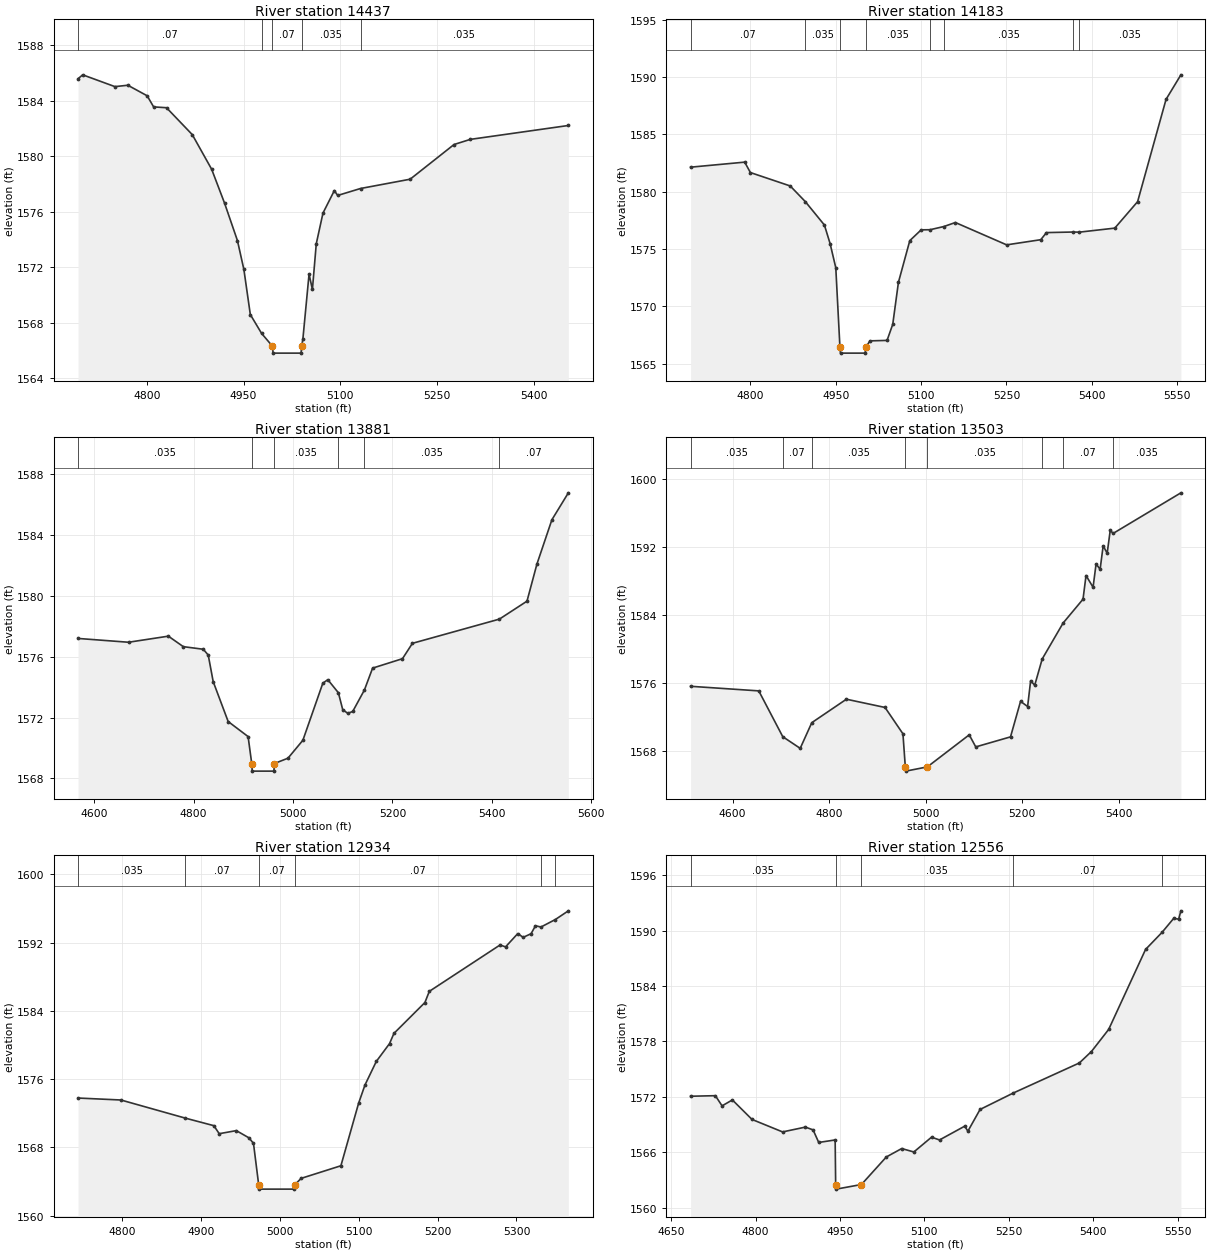
Type RM Length L Ch R = 1,14437,254,254,254
BEGIN DESCRIPTION:
Mapping XS 1fa06b26
END DESCRIPTION:
XS GIS Cut Line= 3
      1630197.82      6954864.52      1630505.07      6954868.00
      1630941.31      6954745.09
#Sta/Elev= 30
  4693.3 1585.58  4700.5 1585.86  4750.5 1585.01  4770.5 1585.11  4800.5 1584.35
  4810.5 1583.55  4830.5 1583.49  4870.5 1581.55  4900.5 1579.06  4920.5 1576.62
  4940.5 1573.92  4950.5 1571.84  4960.5 1568.59  4978.0 1567.23  4994.8 1566.31
  4995.8 1565.81  5039.2 1565.81  5040.2 1566.31  5042.1 1566.86  5051.6 1571.50
  5056.8 1570.40  5062.8 1573.69  5073.2 1575.90  5090.8 1577.52  5096.0 1577.17
  5131.4 1577.67  5208.4 1578.34  5276.5 1580.84  5301.8 1581.21  5453.8 1582.21
#Mann=5,-1,0
  4693.3    0.07       0  4978.0   0.035       0  4994.8    0.07       0
  5040.2   0.035       0  5131.4   0.035       0
Bank Sta=4994.8,5040.2
Exp/Cntr=0.3,0.1

Type RM Length L Ch R = 1,14183,302,302,302
BEGIN DESCRIPTION:
Mapping XS 4ed7eb7b
END DESCRIPTION:
XS GIS Cut Line= 3
      1630150.01      6955094.38      1630454.72      6955106.10
      1631011.04      6955130.80
#Sta/Elev= 30
  4694.8 1582.14  4789.9 1582.58  4799.9 1581.67  4869.9 1580.50  4896.5 1579.13
  4930.0 1577.09  4940.0 1575.47  4950.0 1573.36  4957.3 1566.41  4958.3 1565.91
  5001.7 1565.91  5002.7 1566.41  5010.0 1566.98  5040.1 1567.02  5050.1 1568.42
  5060.1 1572.09  5080.1 1575.73  5100.1 1576.67  5115.7 1576.68  5140.0 1576.96
  5160.2 1577.31  5250.3 1575.36  5310.3 1575.81  5320.3 1576.43  5367.3 1576.48
  5378.2 1576.47  5440.4 1576.82  5480.5 1579.13  5530.5 1588.06  5556.6 1590.20
#Mann=8,-1,0
  4694.8    0.07       0  4896.5   0.035       0  4957.3   0.035       0
  5002.7   0.035       0  5115.7    0.07       0  5140.0   0.035       0
  5367.3    0.07       0  5378.2   0.035       0
Bank Sta=4957.3,5002.7
Exp/Cntr=0.3,0.1

Type RM Length L Ch R = 1,13881,378,378,378
BEGIN DESCRIPTION:
Mapping XS 4a9d9bad
END DESCRIPTION:
XS GIS Cut Line= 3
      1630023.76      6955379.54      1630454.72      6955408.19
      1631008.10      6955438.13
#Sta/Elev= 30
  4567.8 1577.20  4669.3 1576.95  4749.4 1577.35  4779.5 1576.66  4819.6 1576.49
  4829.6 1576.11  4839.6 1574.36  4869.7 1571.74  4909.8 1570.75  4917.1 1568.98
  4918.1 1568.48  4961.7 1568.48  4962.7 1568.98  4990.0 1569.33  5020.0 1570.51
  5060.1 1574.26  5070.1 1574.49  5091.4 1573.63  5100.1 1572.52  5110.2 1572.28
  5120.2 1572.40  5143.7 1573.81  5160.2 1575.25  5220.3 1575.87  5240.3 1576.88
  5415.2 1578.47  5470.7 1579.65  5490.7 1582.09  5520.8 1585.00  5553.9 1586.77
#Mann=6,-1,0
  4567.8   0.035       0  4917.1   0.035       0  4962.7   0.035       0
  5091.4    0.07       0  5143.7   0.035       0  5415.2    0.07       0
Bank Sta=4917.1,4962.7
Exp/Cntr=0.3,0.1

Type RM Length L Ch R = 1,13503,569,569,569
BEGIN DESCRIPTION:
Mapping XS 7179c987
END DESCRIPTION:
XS GIS Cut Line= 3
      1630032.21      6955539.05      1630454.07      6955787.74
      1630875.95      6956101.55
#Sta/Elev= 30
  4513.2 1575.67  4654.4 1575.13  4704.1 1569.74  4740.2 1568.37  4764.2 1571.39
  4835.9 1574.15  4915.9 1573.18  4953.0 1570.08  4957.9 1566.19  4958.9 1565.69
  5003.6 1566.19  5090.3 1569.96  5103.8 1568.54  5175.8 1569.72  5196.6 1573.90
  5211.2 1573.29  5217.5 1576.33  5225.9 1575.79  5241.4 1578.88  5284.7 1583.11
  5326.0 1585.92  5332.2 1588.70  5346.8 1587.32  5353.0 1590.06  5361.4 1589.44
  5367.7 1592.20  5376.0 1591.32  5382.3 1594.00  5388.5 1593.66  5528.7 1598.43
#Mann=8,-1,0
  4513.2   0.035       0  4704.1    0.07       0  4764.2   0.035       0
  4957.9    0.07       0  5003.6   0.035       0  5241.4   0.035       0
  5284.7    0.07       0  5388.5   0.035       0
Bank Sta=4957.9,5003.6
Exp/Cntr=0.3,0.1

Type RM Length L Ch R = 1,12934,378,378,378
BEGIN DESCRIPTION:
Mapping XS f0ae8113
END DESCRIPTION:
XS GIS Cut Line= 3
      1629832.56      6955767.37      1629957.54      6955992.61
      1630118.99      6956319.42
#Sta/Elev= 30
  4743.7 1573.79  4798.1 1573.56  4880.0 1571.43  4916.0 1570.55  4922.8 1569.61
  4944.5 1569.97  4960.6 1569.12  4966.3 1568.47  4972.9 1563.61  4973.9 1563.11
  5017.6 1563.11  5018.6 1563.61  5026.7 1564.37  5077.2 1565.85  5099.6 1573.16
  5107.7 1575.31  5122.1 1578.08  5138.9 1580.17  5144.5 1581.37  5183.8 1584.99
  5189.4 1586.30  5279.2 1591.74  5286.1 1591.51  5301.6 1593.07  5308.5 1592.63
  5318.5 1593.06  5324.1 1593.99  5331.0 1593.84  5349.3 1594.72  5365.8 1595.74
#Mann=6,-1,0
  4743.7   0.035       0  4880.0    0.07       0  4972.9    0.07       0
  5018.6    0.07       0  5331.0   0.035       0  5349.3    0.07       0
Bank Sta=4972.9,5018.6
Exp/Cntr=0.3,0.1

Type RM Length L Ch R = 1,12556,351,351,351
BEGIN DESCRIPTION:
Mapping XS 87e5f40d
END DESCRIPTION:
XS GIS Cut Line= 3
      1629510.05      6955847.40      1629633.32      6956140.83
      1629910.53      6956619.01
#Sta/Elev= 30
  4684.7 1572.07  4728.7 1572.13  4740.6 1571.03  4758.9 1571.67  4793.8 1569.56
  4848.1 1568.21  4888.6 1568.73  4902.3 1568.43  4912.3 1567.07  4941.5 1567.34
  4942.4 1562.52  4943.4 1562.02  4988.2 1562.52  5032.4 1565.50  5059.7 1566.41
  5081.3 1566.04  5112.7 1567.64  5126.9 1567.34  5171.6 1568.83  5177.3 1568.29
  5198.9 1570.64  5258.0 1572.42  5375.3 1575.67  5396.8 1576.91  5427.4 1579.30
  5492.9 1587.95  5522.2 1589.80  5543.0 1591.32  5551.7 1591.23  5555.7 1592.13
#Mann=5,-1,0
  4684.7   0.035       0  4942.4   0.035       0  4988.2   0.035       0
  5258.0    0.07       0  5522.2    0.16       0
Bank Sta=4942.4,4988.2
Exp/Cntr=0.3,0.1

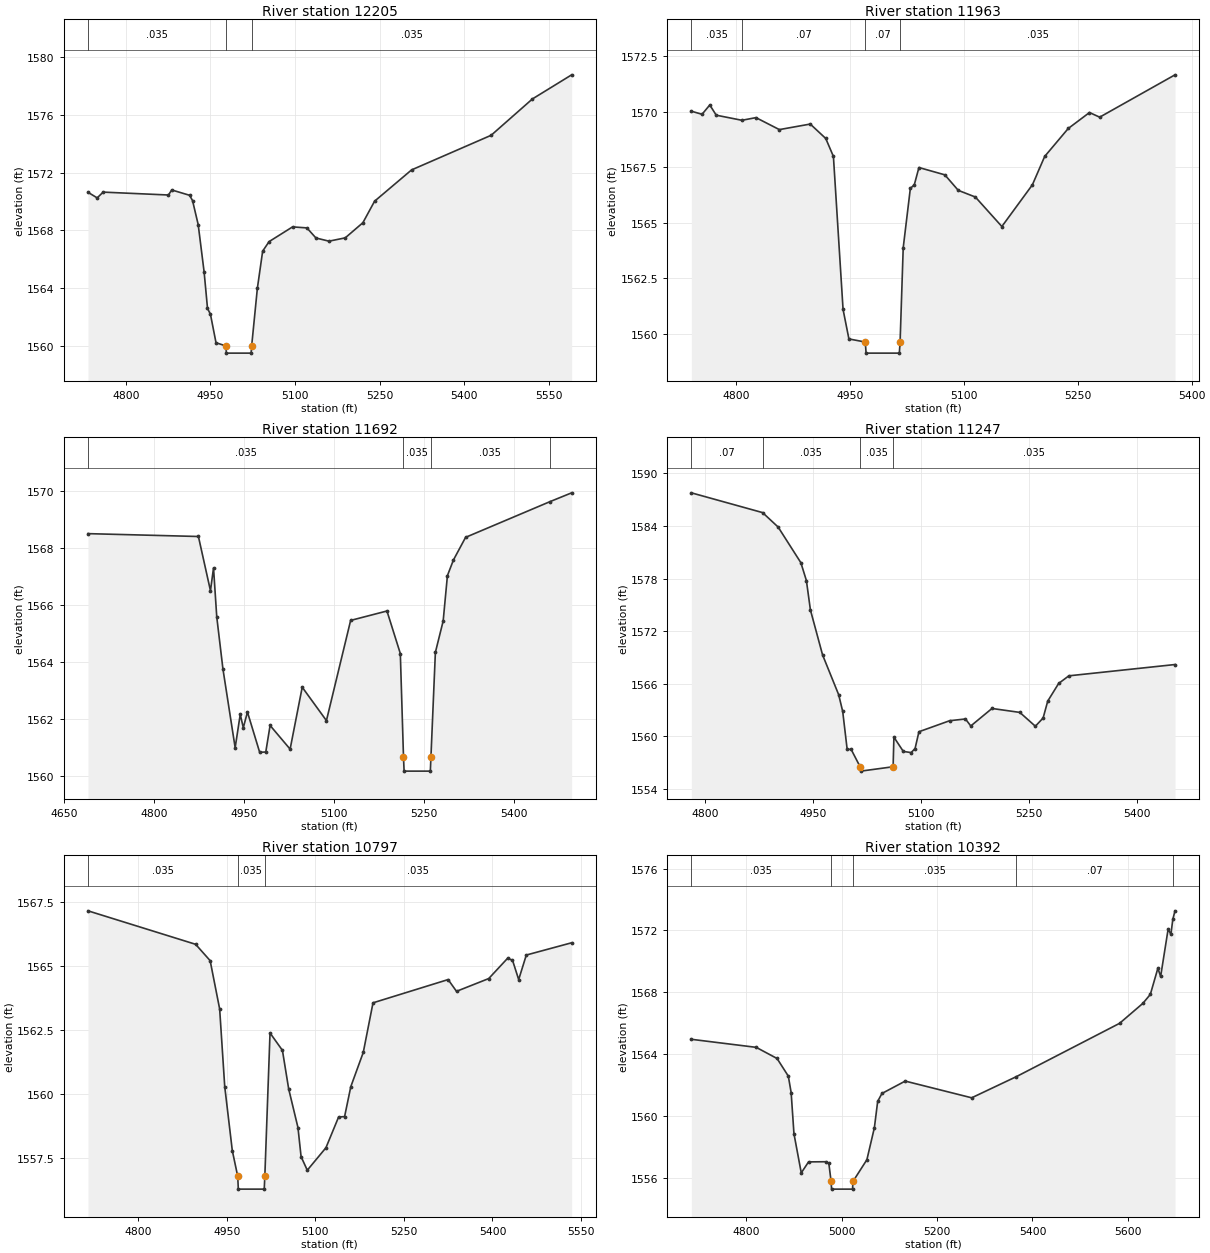
Type RM Length L Ch R = 1,12205,242,242,242
BEGIN DESCRIPTION:
Mapping XS 9a05f0ce
END DESCRIPTION:
XS GIS Cut Line= 3
      1629213.19      6955932.50      1629298.25      6956189.44
      1629457.64      6956754.22
#Sta/Elev= 30
  4732.8 1570.65  4749.1 1570.26  4759.7 1570.66  4875.5 1570.46  4881.3 1570.81
  4913.0 1570.44  4918.2 1570.07  4928.2 1568.41  4938.7 1565.13  4944.7 1562.61
  4950.0 1562.18  4959.8 1560.22  4977.2 1560.00  4978.2 1559.50  5022.0 1559.50
  5023.0 1560.00  5033.1 1563.99  5042.5 1566.57  5053.9 1567.23  5095.5 1568.25
  5120.9 1568.18  5137.0 1567.48  5160.1 1567.26  5188.9 1567.49  5220.2 1568.54
  5240.9 1570.03  5306.5 1572.20  5447.6 1574.60  5520.8 1577.12  5590.3 1578.79
#Mann=3,-1,0
  4732.8   0.035       0  4977.2    0.07       0  5023.0   0.035       0
Bank Sta=4977.2,5023
Exp/Cntr=0.3,0.1

Type RM Length L Ch R = 1,11963,271,271,271
BEGIN DESCRIPTION:
Mapping XS c86bba29
END DESCRIPTION:
XS GIS Cut Line= 3
      1629023.23      6955984.14      1629072.06      6956241.30
      1629168.38      6956603.86
#Sta/Elev= 30
  4741.2 1570.03  4755.3 1569.89  4765.5 1570.31  4774.0 1569.85  4807.8 1569.62
  4826.3 1569.74  4857.1 1569.20  4897.8 1569.45  4918.2 1568.80  4928.3 1567.99
  4941.0 1561.09  4948.7 1559.76  4970.3 1559.62  4971.3 1559.12  5015.1 1559.12
  5016.1 1559.62  5020.2 1563.87  5029.6 1566.55  5034.8 1566.71  5040.9 1567.49
  5075.0 1567.16  5092.7 1566.46  5115.2 1566.16  5150.1 1564.83  5190.3 1566.71
  5206.5 1567.99  5237.5 1569.25  5265.5 1569.97  5278.9 1569.76  5378.1 1571.67
#Mann=4,-1,0
  4741.2   0.035       0  4807.8    0.07       0  4970.3    0.07       0
  5016.1   0.035       0
Bank Sta=4970.3,5016.1
Exp/Cntr=0.3,0.1

Type RM Length L Ch R = 1,11692,445,445,445
BEGIN DESCRIPTION:
Mapping XS 6d7b7479
END DESCRIPTION:
XS GIS Cut Line= 3
      1628736.77      6955927.69      1628801.88      6956235.88
      1628869.96      6956723.26
#Sta/Elev= 30
  4689.9 1568.49  4874.2 1568.39  4894.3 1566.49  4899.4 1567.29  4904.8 1565.57
  4915.1 1563.75  4935.5 1560.99  4944.0 1562.16  4949.1 1561.69  4956.0 1562.24
  4976.4 1560.83  4986.6 1560.84  4993.8 1561.77  5027.2 1560.94  5047.4 1563.11
  5087.8 1561.94  5128.2 1565.45  5188.8 1565.78  5211.1 1564.29  5216.4 1560.67
  5217.4 1560.17  5261.2 1560.17  5262.2 1560.67  5269.6 1564.33  5282.6 1565.43
  5289.7 1567.02  5299.8 1567.57  5320.0 1568.36  5460.7 1569.61  5497.0 1569.92
#Mann=4,-1,0
  4689.9   0.035       0  5216.4   0.035       0  5262.2   0.035       0
  5460.7    0.16       0
Bank Sta=5216.4,5262.2
Exp/Cntr=0.3,0.1

Type RM Length L Ch R = 1,11247,450,450,450
BEGIN DESCRIPTION:
Mapping XS 4722bbe3
END DESCRIPTION:
XS GIS Cut Line= 3
      1628388.24      6956161.43      1628485.47      6956358.49
      1628656.50      6956777.81
#Sta/Elev= 30
  4780.9 1587.79  4880.0 1585.53  4901.6 1583.88  4933.2 1579.81  4940.9 1577.77
  4946.5 1574.41  4963.4 1569.27  4985.8 1564.72  4991.4 1562.81  4997.6 1558.48
  5003.1 1558.48  5015.6 1556.49  5016.6 1555.99  5061.5 1556.49  5062.6 1559.87
  5075.7 1558.24  5086.5 1558.11  5092.0 1558.56  5097.4 1560.49  5140.1 1561.75
  5162.1 1561.95  5169.5 1561.15  5199.0 1563.15  5237.7 1562.70  5259.3 1561.12
  5270.1 1562.06  5276.5 1563.99  5291.7 1566.01  5305.9 1566.88  5453.5 1568.17
#Mann=4,-1,0
  4780.9    0.07       0  4880.0   0.035       0  5015.6   0.035       0
  5061.5   0.035       0
Bank Sta=5015.6,5061.5
Exp/Cntr=0.3,0.1

Type RM Length L Ch R = 1,10797,405,405,405
BEGIN DESCRIPTION:
Mapping XS d4b6bd47
END DESCRIPTION:
XS GIS Cut Line= 3
      1627995.88      6956269.79      1628097.88      6956535.65
      1628264.91      6957043.22
#Sta/Elev= 30
  4715.0 1567.17  4897.3 1565.86  4921.9 1565.22  4938.0 1563.33  4946.6 1560.29
  4959.4 1557.79  4968.6 1556.78  4969.6 1556.28  5013.5 1556.28  5014.5 1556.78
  5023.3 1562.39  5044.3 1561.71  5054.9 1560.20  5070.6 1558.69  5075.9 1557.55
  5086.4 1557.02  5118.0 1557.90  5139.4 1559.10  5149.6 1559.12  5160.1 1560.29
  5181.2 1561.63  5197.7 1563.57  5324.9 1564.48  5339.1 1564.02  5393.7 1564.52
  5425.5 1565.31  5433.9 1565.24  5444.4 1564.48  5457.3 1565.44  5534.1 1565.92
#Mann=3,-1,0
  4715.0   0.035       0  4968.6   0.035       0  5014.5   0.035       0
Bank Sta=4968.6,5014.5
Exp/Cntr=0.3,0.1

Type RM Length L Ch R = 1,10392,342,342,342
BEGIN DESCRIPTION:
Mapping XS 5702df65
END DESCRIPTION:
XS GIS Cut Line= 3
      1627589.26      6956425.65      1627756.78      6956693.86
      1628106.32      6957296.97
#Sta/Elev= 30
  4685.3 1564.97  4821.2 1564.45  4864.9 1563.73  4888.5 1562.59  4894.4 1561.53
  4900.3 1558.87  4915.6 1556.34  4930.9 1557.05  4967.5 1557.06  4973.4 1556.95
  4978.1 1555.79  4979.1 1555.29  5023.0 1555.29  5024.0 1555.79  5053.1 1557.19
  5068.8 1559.26  5075.7 1560.96  5084.6 1561.47  5133.4 1562.27  5272.6 1561.19
  5366.4 1562.56  5582.4 1566.00  5631.2 1567.29  5646.9 1567.87  5662.7 1569.56
  5668.5 1569.03  5684.2 1572.09  5690.0 1571.75  5694.0 1572.72  5698.6 1573.27
#Mann=5,-1,0
  4685.3   0.035       0  4978.1   0.035       0  5024.0   0.035       0
  5366.4    0.07       0  5694.0   0.035       0
Bank Sta=4978.1,5024
Exp/Cntr=0.3,0.1

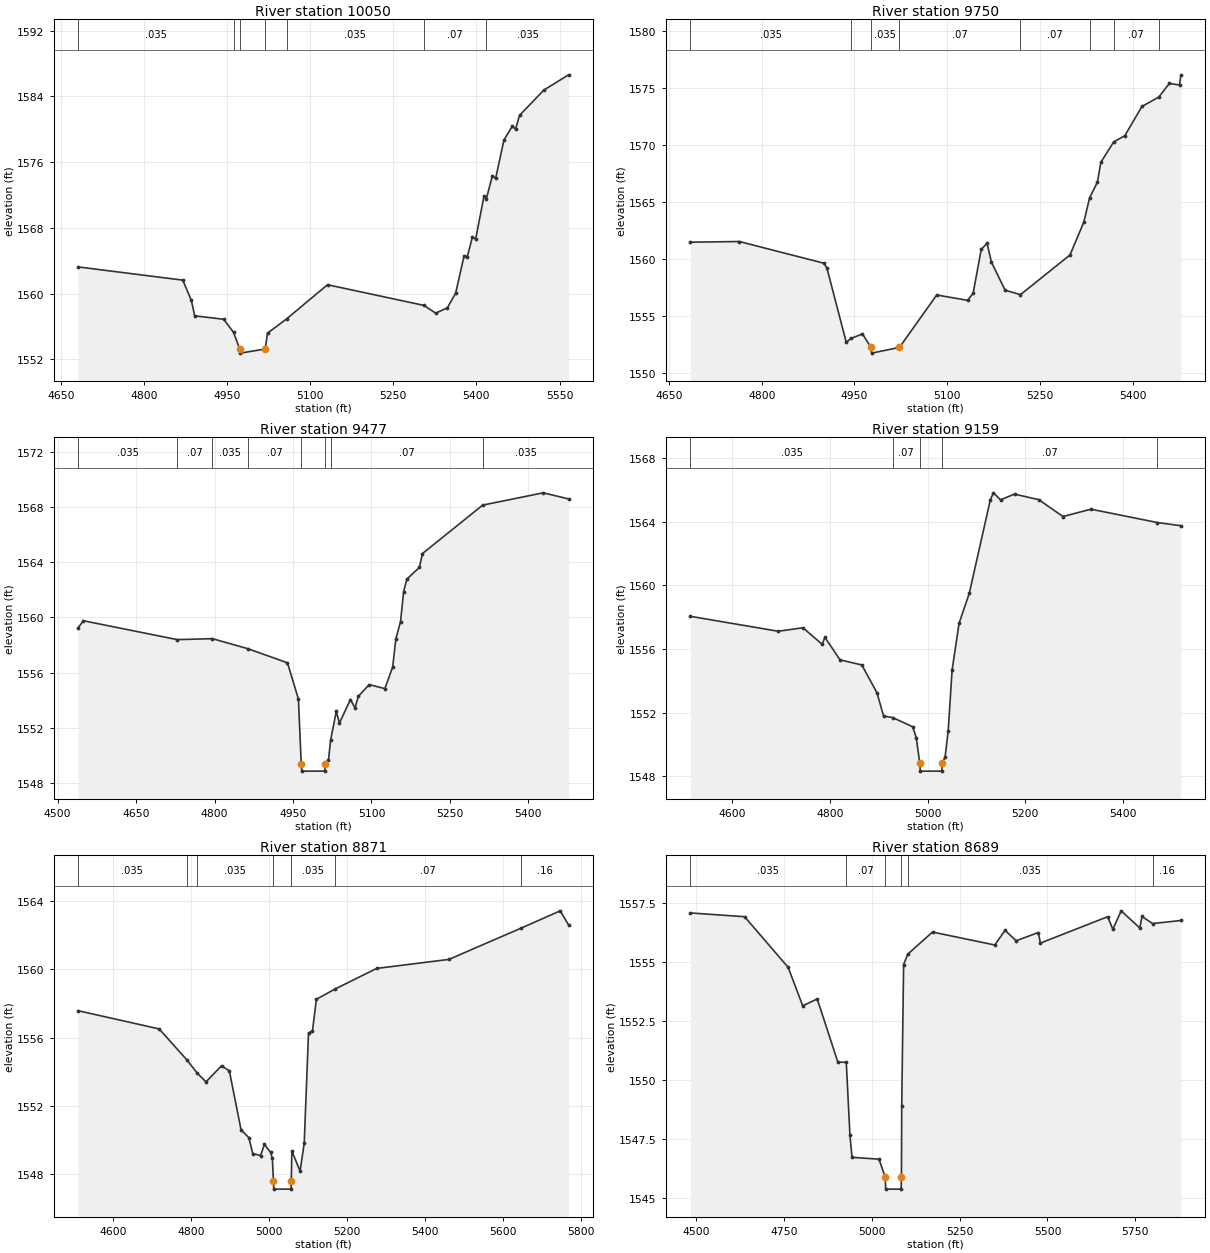
Type RM Length L Ch R = 1,10050,300,300,300
BEGIN DESCRIPTION:
Mapping XS 3ca1c72b
END DESCRIPTION:
XS GIS Cut Line= 3
      1627294.49      6956557.80      1627459.42      6956831.22
      1627773.66      6957301.60
#Sta/Elev= 30
  4681.3 1563.24  4870.2 1561.63  4885.7 1559.17  4891.7 1557.29  4944.0 1556.87
  4961.8 1555.28  4972.9 1553.25  4973.9 1552.75  5018.8 1553.25  5023.2 1555.18
  5057.4 1556.91  5131.4 1561.07  5305.2 1558.56  5326.6 1557.61  5347.6 1558.27
  5362.6 1560.05  5377.6 1564.54  5383.6 1564.50  5392.6 1566.82  5398.7 1566.65
  5413.7 1571.85  5418.0 1571.53  5428.7 1574.31  5434.7 1574.01  5449.7 1578.68
  5464.7 1580.35  5470.7 1580.01  5477.8 1581.68  5521.8 1584.76  5566.3 1586.61
#Mann=7,-1,0
  4681.3   0.035       0  4961.8    0.07       0  4972.9    0.07       0
  5018.8    0.07       0  5057.4   0.035       0  5305.2    0.07       0
  5418.0   0.035       0
Bank Sta=4972.9,5018.8
Exp/Cntr=0.3,0.1

Type RM Length L Ch R = 1,9750,273,273,273
BEGIN DESCRIPTION:
Mapping XS e7d081d1
END DESCRIPTION:
XS GIS Cut Line= 3
      1627130.00      6956713.01      1627230.95      6957013.15
      1627450.36      6957436.28
#Sta/Elev= 30
  4684.6 1561.47  4763.7 1561.53  4899.9 1559.63  4905.2 1559.24  4936.7 1552.67
  4944.5 1553.01  4962.9 1553.41  4976.7 1552.22  4977.7 1551.72  5022.7 1552.22
  5083.0 1556.83  5132.9 1556.36  5141.9 1556.98  5155.0 1560.84  5164.4 1561.37
  5171.5 1559.72  5193.6 1557.25  5218.5 1556.86  5298.6 1560.35  5320.8 1563.22
  5330.3 1565.37  5342.9 1566.75  5348.5 1568.50  5369.2 1570.28  5387.2 1570.83
  5414.9 1573.40  5442.1 1574.22  5459.2 1575.42  5475.7 1575.29  5477.9 1576.18
#Mann=8,-1,0
  4684.6   0.035       0  4944.5    0.07       0  4976.7   0.035       0
  5022.7    0.07       0  5218.5    0.07       0  5330.3   0.035       0
  5369.2    0.07       0  5442.1   0.035       0
Bank Sta=4976.7,5022.7
Exp/Cntr=0.3,0.1

Type RM Length L Ch R = 1,9477,318,318,318
BEGIN DESCRIPTION:
Mapping XS 0a2ca7aa
END DESCRIPTION:
XS GIS Cut Line= 3
      1626796.34      6956891.84      1627100.74      6957241.01
      1627366.78      6957634.00
#Sta/Elev= 30
  4539.0 1559.24  4549.2 1559.76  4728.7 1558.39  4795.8 1558.46  4863.9 1557.73
  4939.4 1556.71  4960.3 1554.08  4965.7 1549.36  4966.7 1548.86  5010.7 1548.86
  5011.7 1549.36  5017.7 1549.65  5021.9 1551.12  5032.7 1553.19  5038.7 1552.34
  5059.7 1554.05  5068.6 1553.44  5074.7 1554.28  5095.7 1555.13  5125.6 1554.84
  5140.5 1556.41  5146.6 1558.45  5155.5 1559.69  5161.5 1561.87  5167.7 1562.78
  5191.5 1563.62  5197.5 1564.63  5312.6 1568.14  5428.2 1569.03  5476.8 1568.59
#Mann=8,-1,0
  4539.0   0.035       0  4728.7    0.07       0  4795.8   0.035       0
  4863.9    0.07       0  4965.7   0.035       0  5011.7    0.07       0
  5021.9    0.07       0  5312.6   0.035       0
Bank Sta=4965.7,5011.7
Exp/Cntr=0.3,0.1

Type RM Length L Ch R = 1,9159,288,288,288
BEGIN DESCRIPTION:
Mapping XS b3585eec
END DESCRIPTION:
XS GIS Cut Line= 3
      1626729.99      6957062.98      1626944.35      6957499.48
      1627346.57      6957825.89
#Sta/Elev= 30
  4514.3 1558.06  4694.2 1557.12  4744.7 1557.34  4784.1 1556.30  4789.7 1556.74
  4820.7 1555.32  4865.3 1555.00  4896.5 1553.24  4909.8 1551.79  4928.2 1551.69
  4969.6 1551.11  4976.7 1550.43  4984.0 1548.82  4985.0 1548.32  5029.0 1548.32
  5030.0 1548.82  5035.8 1549.20  5042.2 1550.86  5050.2 1554.69  5064.5 1557.63
  5085.3 1559.50  5128.5 1565.40  5134.9 1565.83  5149.3 1565.39  5178.0 1565.75
  5227.6 1565.40  5277.1 1564.34  5334.6 1564.80  5470.5 1563.96  5518.6 1563.76
#Mann=5,-1,0
  4514.3   0.035       0  4928.2    0.07       0  4984.0    0.07       0
  5030.0    0.07       0  5470.5    0.16       0
Bank Sta=4984,5030
Exp/Cntr=0.3,0.1

Type RM Length L Ch R = 1,8871,182,182,182
BEGIN DESCRIPTION:
Mapping XS d6b90d34
END DESCRIPTION:
XS GIS Cut Line= 3
      1626694.53      6957149.79      1626711.27      6957641.40
      1627435.12      6957896.86
#Sta/Elev= 30
  4509.2 1557.58  4717.5 1556.51  4787.9 1554.71  4815.1 1553.92  4837.6 1553.40
  4877.6 1554.35  4897.6 1554.05  4927.7 1550.59  4947.7 1550.13  4957.7 1549.20
  4977.7 1549.08  4987.7 1549.73  5003.5 1549.27  5008.1 1548.93  5010.8 1547.61
  5011.8 1547.11  5055.8 1547.11  5056.8 1547.61  5058.1 1549.35  5079.3 1548.17
  5089.9 1549.80  5100.9 1556.27  5111.1 1556.40  5121.2 1558.25  5169.8 1558.86
  5275.9 1560.06  5461.5 1560.59  5646.4 1562.42  5747.4 1563.44  5768.7 1562.61
#Mann=7,-1,0
  4509.2   0.035       0  4787.9    0.07       0  4815.1   0.035       0
  5010.8   0.035       0  5056.8   0.035       0  5169.8    0.07       0
  5646.4    0.16       0
Bank Sta=5010.8,5056.8
Exp/Cntr=0.3,0.1

Type RM Length L Ch R = 1,8689,493,493,493
BEGIN DESCRIPTION:
Mapping XS 46651867
END DESCRIPTION:
XS GIS Cut Line= 3
      1626677.17      6957188.82      1626545.93      6957688.05
      1627357.18      6958028.53
#Sta/Elev= 30
  4483.8 1557.09  4638.1 1556.93  4762.1 1554.78  4803.5 1553.15  4844.8 1553.44
  4903.5 1550.76  4927.5 1550.75  4937.9 1547.66  4943.9 1546.72  5020.7 1546.64
  5038.5 1545.87  5039.5 1545.37  5083.5 1545.37  5084.5 1545.87  5085.3 1548.91
  5090.7 1554.90  5102.4 1555.34  5172.9 1556.28  5350.1 1555.73  5379.3 1556.35
  5411.1 1555.91  5474.3 1556.26  5479.8 1555.81  5671.4 1556.93  5686.1 1556.40
  5709.9 1557.18  5762.9 1556.45  5769.0 1556.94  5799.3 1556.64  5879.8 1556.77
#Mann=6,-1,0
  4483.8   0.035       0  4927.5    0.07       0  5038.5    0.07       0
  5084.5    0.07       0  5102.4   0.035       0  5799.3    0.16       0
Bank Sta=5038.5,5084.5
Exp/Cntr=0.3,0.1