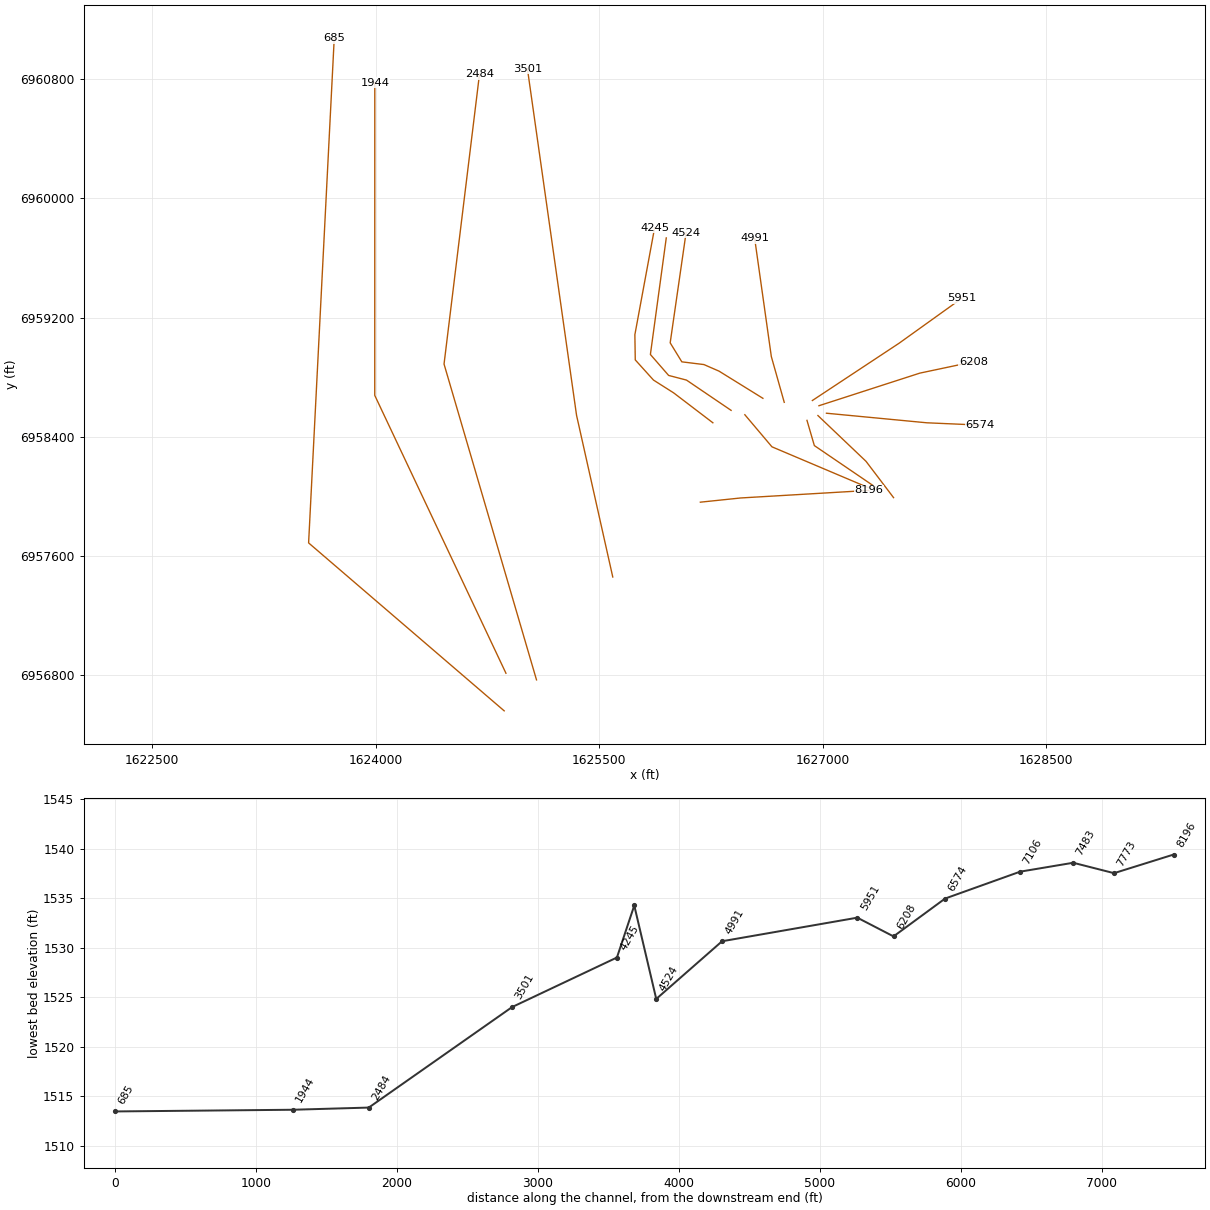
HEC-RAS study Chimney Creek.prj: Chimney Creek Base Level Engineering

--- Chimney Creek.g01 (geometry) --- (continued)

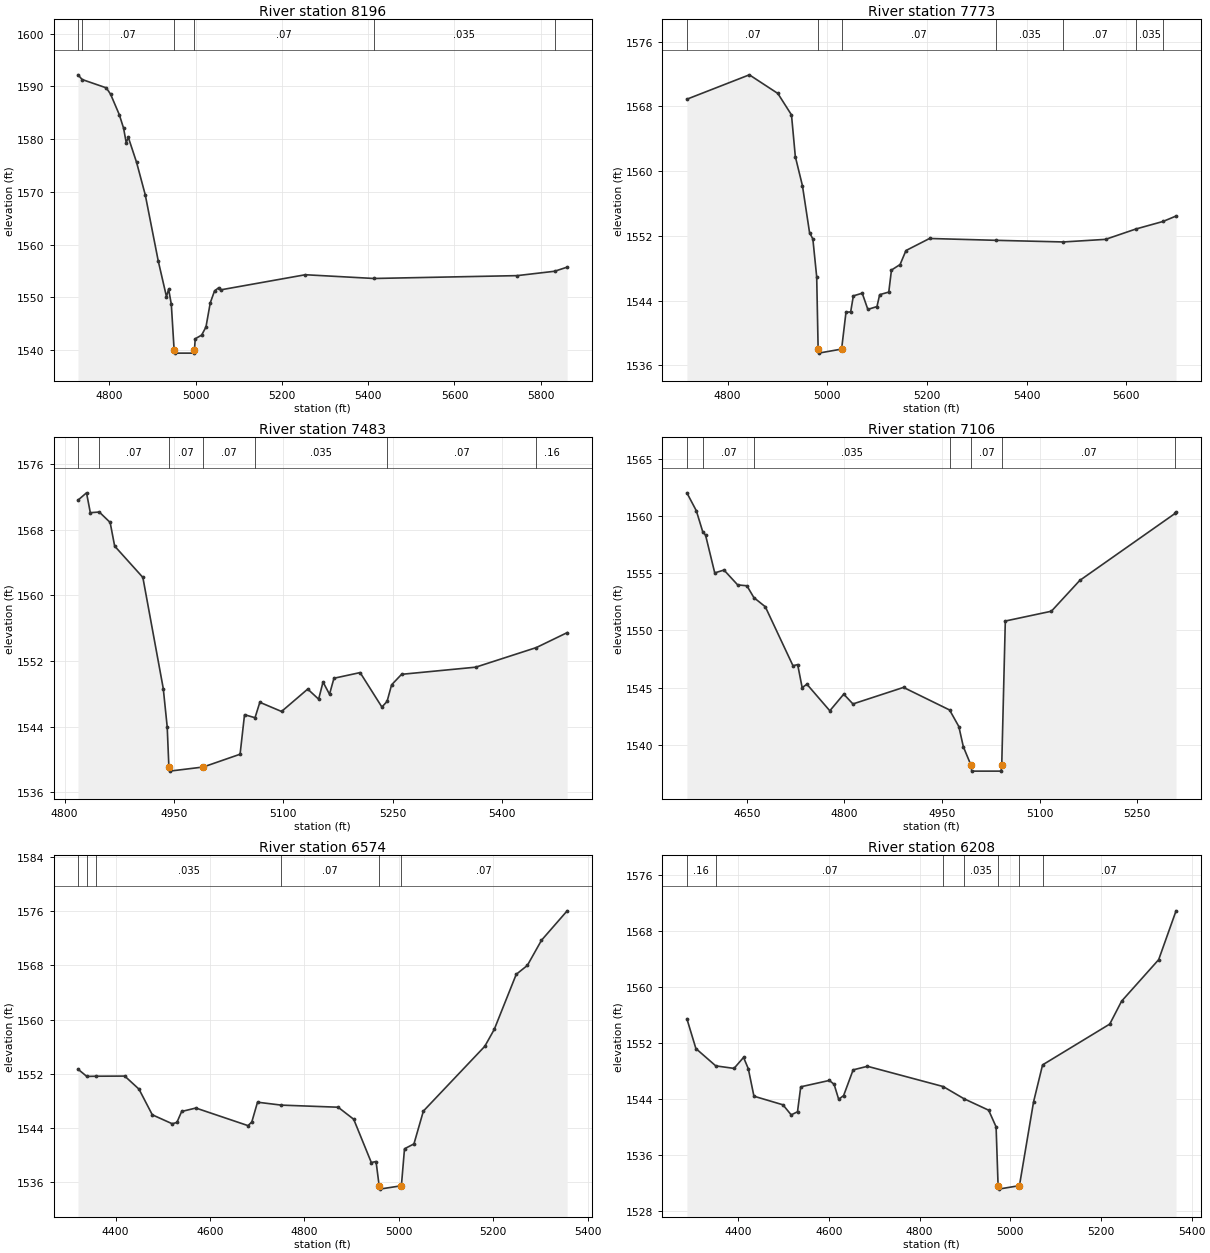
Type RM Length L Ch R = 1,8196,423,423,423
BEGIN DESCRIPTION:
Mapping XS d0c11abc
END DESCRIPTION:
XS GIS Cut Line= 3
      1626179.90      6957961.31      1626450.27      6957989.52
      1627310.84      6958040.21
#Sta/Elev= 30
  4727.3 1592.19  4736.9 1591.30  4792.8 1589.72  4802.8 1588.52  4822.9 1584.66
  4833.0 1582.06  4839.0 1579.34  4844.0 1580.31  4863.1 1575.58  4883.2 1569.43
  4913.4 1556.85  4932.4 1550.11  4937.4 1551.54  4943.6 1548.66  4950.2 1539.90
  4951.2 1539.40  4996.2 1539.40  4997.2 1539.90  4999.0 1542.12  5013.9 1542.82
  5023.9 1544.35  5033.9 1548.94  5043.9 1551.22  5053.6 1551.81  5058.6 1551.41
  5254.3 1554.27  5413.1 1553.56  5745.2 1554.10  5832.1 1554.93  5861.2 1555.71
#Mann=6,-1,0
  4727.3   0.035       0  4736.9    0.07       0  4950.2    0.07       0
  4997.2    0.07       0  5413.1   0.035       0  5832.1    0.16       0
Bank Sta=4950.2,4997.2
Exp/Cntr=0.3,0.1

Type RM Length L Ch R = 1,7773,290,290,290
BEGIN DESCRIPTION:
Mapping XS 5765c4ba
END DESCRIPTION:
XS GIS Cut Line= 3
      1626478.50      6958548.14      1626660.44      6958332.82
      1627305.11      6958059.79
#Sta/Elev= 30
  4718.1 1568.88  4843.5 1571.89  4900.7 1569.59  4928.1 1566.94  4935.8 1561.79
  4950.1 1558.19  4964.4 1552.39  4971.0 1551.62  4978.7 1546.94  4981.6 1538.02
  4982.6 1537.52  5028.7 1538.02  5037.5 1542.57  5046.9 1542.61  5052.3 1544.59
  5070.1 1544.92  5081.4 1542.92  5099.7 1543.27  5105.1 1544.74  5123.4 1545.06
  5128.8 1547.78  5146.1 1548.46  5157.9 1550.19  5205.3 1551.68  5339.3 1551.45
  5473.8 1551.25  5558.5 1551.57  5619.5 1552.85  5673.9 1553.78  5700.1 1554.45
#Mann=7,-1,0
  4718.1    0.07       0  4981.6    0.07       0  5028.7    0.07       0
  5339.3   0.035       0  5473.8    0.07       0  5619.5   0.035       0
  5673.9    0.16       0
Bank Sta=4981.6,5028.7
Exp/Cntr=0.3,0.1

Type RM Length L Ch R = 1,7483,377,377,377
BEGIN DESCRIPTION:
Mapping XS d05ff261
END DESCRIPTION:
XS GIS Cut Line= 3
      1626895.59      6958510.34      1626945.07      6958341.08
      1627354.18      6958062.68
#Sta/Elev= 30
  4818.3 1571.60  4830.0 1572.49  4835.2 1570.07  4847.5 1570.15  4862.4 1568.88
  4868.6 1566.00  4907.3 1562.18  4935.3 1548.64  4940.7 1543.96  4943.0 1539.07
  4944.0 1538.57  4990.1 1539.07  5040.7 1540.63  5046.8 1545.45  5061.2 1545.08
  5067.8 1546.96  5097.6 1545.84  5133.5 1548.57  5148.5 1547.34  5154.5 1549.43
  5163.4 1547.94  5169.5 1549.89  5205.4 1550.58  5235.3 1546.38  5242.4 1547.07
  5248.6 1549.09  5262.3 1550.37  5364.0 1551.24  5447.2 1553.63  5489.5 1555.45
#Mann=7,-1,0
  4818.3    0.16       0  4847.5    0.07       0  4943.0    0.07       0
  4990.1    0.07       0  5061.2   0.035       0  5242.4    0.07       0
  5447.2    0.16       0
Bank Sta=4943,4990.1
Exp/Cntr=0.3,0.1

Type RM Length L Ch R = 1,7106,532,532,532
BEGIN DESCRIPTION:
Mapping XS e7090f62
END DESCRIPTION:
XS GIS Cut Line= 3
      1626969.09      6958542.61      1627292.00      6958235.33
      1627476.82      6957991.77
#Sta/Elev= 30
  4558.0 1562.07  4572.5 1560.50  4582.3 1558.67  4586.7 1558.36  4600.8 1555.05
  4615.0 1555.30  4636.0 1554.00  4650.2 1553.92  4661.0 1552.88  4678.5 1552.08
  4721.0 1546.91  4728.2 1547.01  4735.1 1544.99  4742.4 1545.29  4777.6 1542.96
  4799.0 1544.42  4813.1 1543.56  4890.8 1545.01  4961.6 1543.03  4975.8 1541.58
  4982.7 1539.81  4994.6 1538.17  4995.6 1537.67  5040.7 1537.67  5041.7 1538.17
  5047.2 1550.83  5118.0 1551.69  5161.6 1554.39  5308.2 1560.27  5309.5 1560.38
#Mann=7,-1,0
  4558.0    0.16       0  4582.3    0.07       0  4661.0   0.035       0
  4961.6    0.07       0  4994.6    0.07       0  5041.7    0.07       0
  5308.2    0.16       0
Bank Sta=4994.6,5041.7
Exp/Cntr=0.3,0.1

Type RM Length L Ch R = 1,6574,366,366,366
BEGIN DESCRIPTION:
Mapping XS 89ed68e1
END DESCRIPTION:
XS GIS Cut Line= 3
      1627026.41      6958558.24      1627699.99      6958494.01
      1628059.31      6958478.38
#Sta/Elev= 30
  4320.4 1552.68  4339.0 1551.61  4359.4 1551.64  4419.4 1551.66  4449.6 1549.73
  4477.8 1545.94  4519.9 1544.62  4529.9 1544.81  4540.0 1546.43  4570.1 1546.94
  4680.6 1544.34  4688.6 1544.88  4700.7 1547.80  4751.0 1547.37  4871.5 1547.06
  4904.5 1545.28  4941.8 1538.89  4951.8 1539.04  4958.4 1535.46  4959.4 1534.96
  5005.5 1535.46  5012.1 1540.92  5032.1 1541.64  5052.1 1546.49  5182.2 1556.06
  5202.2 1558.55  5248.8 1566.69  5272.3 1568.00  5302.3 1571.72  5356.7 1576.07
#Mann=6,-1,0
  4320.4    0.16       0  4339.0    0.07       0  4359.4   0.035       0
  4751.0    0.07       0  4958.4    0.07       0  5005.5    0.07       0
Bank Sta=4958.4,5005.5
Exp/Cntr=0.3,0.1

Type RM Length L Ch R = 1,6208,257,257,257
BEGIN DESCRIPTION:
Mapping XS a3a90979
END DESCRIPTION:
XS GIS Cut Line= 3
      1626976.03      6958608.59      1627653.11      6958827.34
      1628012.51      6958903.37
#Sta/Elev= 30
  4286.7 1555.47  4306.6 1551.21  4350.4 1548.74  4390.7 1548.38  4411.7 1549.95
  4422.2 1548.33  4434.6 1544.41  4498.6 1543.18  4516.8 1541.74  4530.7 1542.19
  4537.8 1545.75  4600.9 1546.66  4611.4 1546.11  4621.5 1543.97  4632.4 1544.50
  4653.4 1548.17  4685.0 1548.68  4851.9 1545.79  4898.1 1544.04  4952.3 1542.41
  4968.7 1540.03  4973.1 1531.64  4974.1 1531.14  5020.2 1531.64  5051.3 1543.59
  5071.2 1548.88  5219.4 1554.71  5245.5 1557.98  5327.3 1563.91  5365.6 1570.88
#Mann=7,-1,0
  4286.7    0.16       0  4350.4    0.07       0  4851.9    0.16       0
  4898.1   0.035       0  4973.1   0.035       0  5020.2   0.035       0
  5071.2    0.07       0
Bank Sta=4973.1,5020.2
Exp/Cntr=0.3,0.1

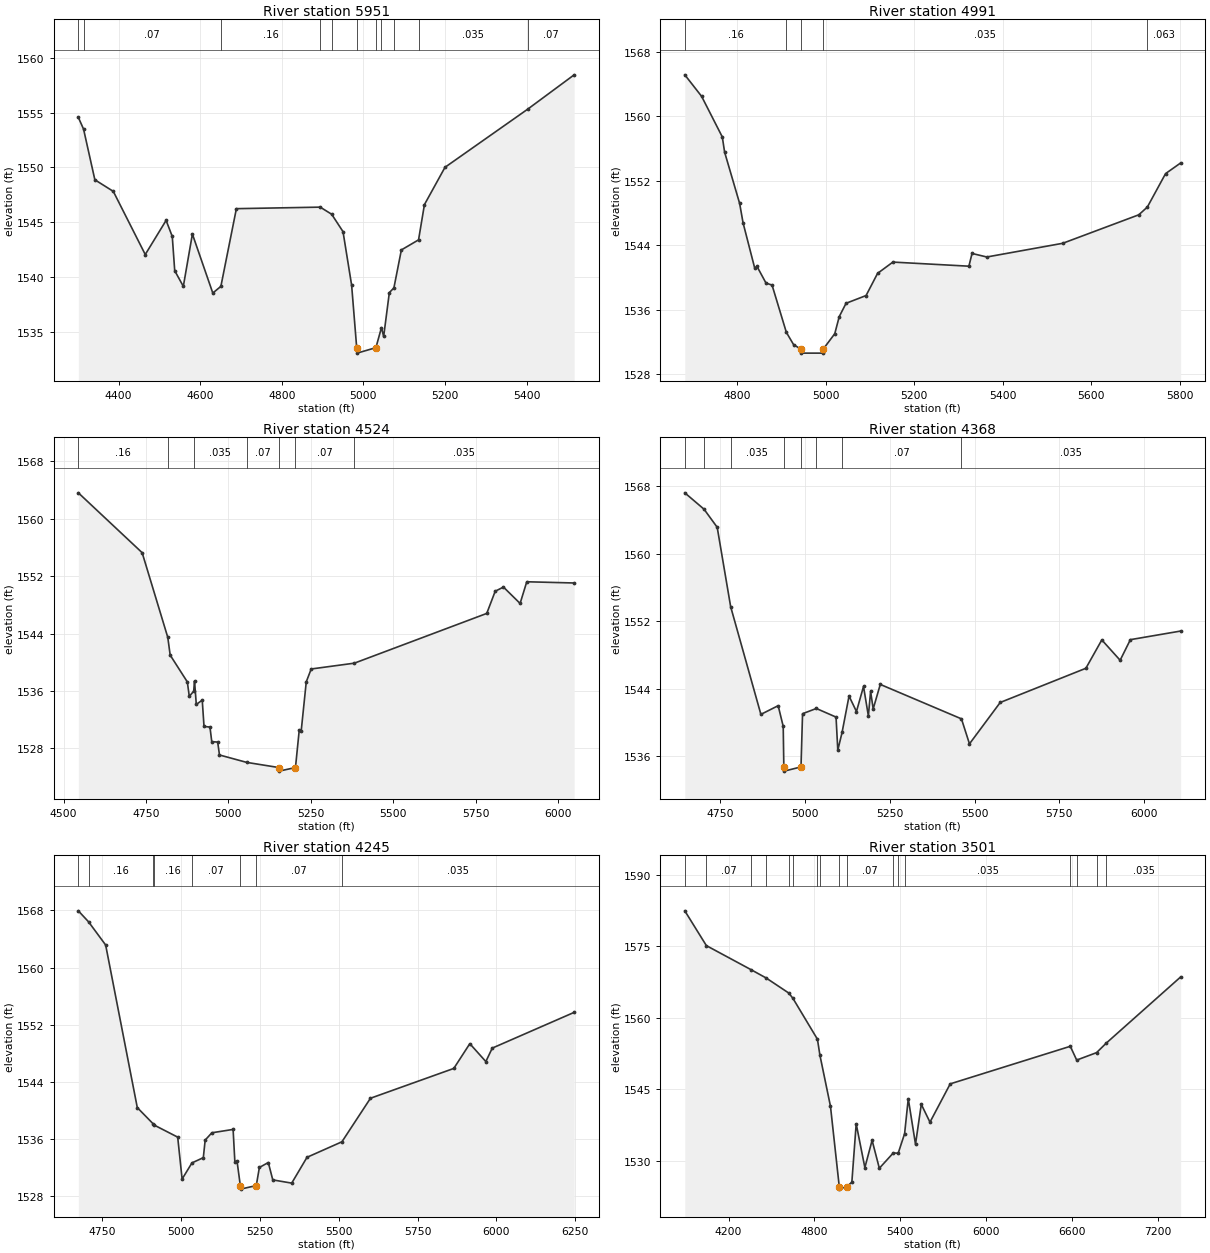
Type RM Length L Ch R = 1,5951,960,960,960
BEGIN DESCRIPTION:
Mapping XS 5a101a8d
END DESCRIPTION:
XS GIS Cut Line= 3
      1626931.81      6958643.55      1627513.44      6959027.69
      1627934.49      6959329.36
#Sta/Elev= 30
  4301.4 1554.57  4314.2 1553.50  4341.9 1548.87  4387.1 1547.81  4465.4 1542.04
  4516.5 1545.16  4531.6 1543.69  4537.6 1540.56  4558.7 1539.13  4580.9 1543.91
  4630.9 1538.52  4650.7 1539.13  4688.7 1546.23  4894.1 1546.37  4922.2 1545.72
  4950.0 1544.13  4971.1 1539.24  4983.5 1533.53  4984.5 1533.03  5030.6 1533.53
  5044.2 1535.36  5049.6 1534.55  5063.5 1538.56  5074.7 1538.99  5093.0 1542.46
  5135.1 1543.38  5149.5 1546.60  5199.9 1550.01  5402.5 1555.32  5516.4 1558.46
#Mann=11,-1,0
  4301.4    0.16       0  4314.2    0.07       0  4650.7    0.16       0
  4894.1   0.035       0  4922.2    0.07       0  4983.5    0.07       0
  5030.6    0.07       0  5044.2   0.035       0  5074.7    0.07       0
  5135.1   0.035       0  5402.5    0.07       0
Bank Sta=4983.5,5030.6
Exp/Cntr=0.3,0.1

Type RM Length L Ch R = 1,4991,467,467,467
BEGIN DESCRIPTION:
Mapping XS d0c2f679
END DESCRIPTION:
XS GIS Cut Line= 3
      1626742.99      6958631.40      1626656.43      6958938.01
      1626544.45      6959731.65
#Sta/Elev= 30
  4681.4 1565.16  4719.4 1562.49  4766.1 1557.46  4771.4 1555.56  4805.3 1549.21
  4813.0 1546.81  4839.3 1541.20  4844.5 1541.40  4864.9 1539.33  4878.5 1539.09
  4910.8 1533.23  4927.2 1531.70  4943.5 1531.15  4944.5 1530.65  4993.1 1530.65
  4994.1 1531.15  5020.2 1533.06  5030.3 1535.18  5045.7 1536.83  5090.9 1537.79
  5116.9 1540.54  5151.5 1541.94  5323.2 1541.43  5330.3 1543.01  5363.6 1542.57
  5535.2 1544.27  5706.9 1547.80  5726.3 1548.76  5767.5 1552.91  5801.5 1554.23
#Mann=5,-1,0
  4681.4    0.16       0  4910.8   0.035       0  4943.5   0.035       0
  4994.1   0.035       0  5726.3   0.063       0
Bank Sta=4943.5,4994.1
Exp/Cntr=0.3,0.1

Type RM Length L Ch R = 1,4524,156,156,156
BEGIN DESCRIPTION:
Mapping XS d0b52acb
END DESCRIPTION:
XS GIS Cut Line= 6
      1626599.79      6958658.23      1626305.53      6958840.52
      1626203.96      6958884.79      1626055.53      6958903.02
      1625977.40      6959030.62      1626084.18      6959770.24
#Sta/Elev= 30
  4544.9 1563.60  4738.4 1555.26  4816.1 1543.47  4823.4 1540.99  4875.4 1537.26
  4881.3 1535.25  4894.7 1535.96  4897.2 1537.39  4902.6 1534.12  4920.6 1534.72
  4926.0 1531.05  4944.0 1530.97  4949.5 1528.93  4967.4 1528.88  4972.9 1527.08
  5055.2 1526.05  5152.7 1525.33  5153.7 1524.83  5203.3 1525.33  5214.7 1530.54
  5220.6 1530.40  5236.0 1537.27  5251.0 1539.06  5381.8 1539.87  5783.3 1546.80
  5808.9 1549.89  5833.9 1550.47  5884.4 1548.19  5904.6 1551.21  6048.3 1551.04
#Mann=7,-1,0
  4544.9    0.16       0  4816.1    0.07       0  4894.7   0.035       0
  5055.2    0.07       0  5152.7   0.035       0  5203.3    0.07       0
  5381.8   0.035       0
Bank Sta=5152.7,5203.3
Exp/Cntr=0.3,0.1

Type RM Length L Ch R = 1,4368,123,123,123
BEGIN DESCRIPTION:
Mapping XS f0385faa
END DESCRIPTION:
XS GIS Cut Line= 5
      1626386.24      6958577.51      1626086.78      6958780.62
      1625966.98      6958811.87      1625844.59      6958952.50
      1625951.13      6959734.70
#Sta/Elev= 30
  4646.0 1567.22  4702.7 1565.28  4741.5 1563.14  4781.2 1553.73  4870.3 1540.98
  4921.2 1542.01  4936.1 1539.56  4937.9 1534.76  4938.9 1534.26  4988.5 1534.76
  4993.1 1541.06  5033.7 1541.68  5091.8 1540.66  5097.0 1536.74  5109.6 1538.85
  5130.1 1543.15  5152.0 1541.32  5172.8 1544.29  5187.1 1540.80  5193.7 1543.70
  5201.3 1541.63  5222.2 1544.53  5461.5 1540.45  5485.1 1537.49  5575.7 1542.39
  5828.2 1546.44  5875.2 1549.80  5929.2 1547.39  5959.4 1549.83  6107.5 1550.85
#Mann=8,-1,0
  4646.0    0.07       0  4702.7    0.16       0  4781.2   0.035       0
  4937.9    0.07       0  4988.5   0.035       0  5033.7   0.035       0
  5109.6    0.07       0  5461.5   0.035       0
Bank Sta=4937.9,4988.5
Exp/Cntr=0.3,0.1

Type RM Length L Ch R = 1,4245,744,744,744
BEGIN DESCRIPTION:
Mapping XS ab9d8975
END DESCRIPTION:
XS GIS Cut Line= 6
      1626263.83      6958494.19      1626000.84      6958694.69
      1625865.42      6958780.62      1625743.03      6958916.04
      1625740.42      6959085.31      1625873.14      6959803.54
#Sta/Elev= 30
  4673.7 1567.93  4706.2 1566.39  4760.4 1563.15  4860.8 1540.41  4910.5 1538.17
  4914.3 1537.97  4989.0 1536.28  5003.0 1530.42  5034.3 1532.68  5070.3 1533.41
  5076.2 1535.87  5097.4 1536.89  5164.8 1537.36  5170.4 1532.82  5177.2 1532.95
  5187.7 1529.51  5188.7 1529.01  5238.3 1529.51  5248.2 1532.04  5276.5 1532.73
  5290.7 1530.30  5350.8 1529.85  5399.3 1533.46  5510.1 1535.63  5600.7 1541.72
  5865.1 1545.89  5915.9 1549.35  5966.8 1546.85  5987.1 1548.73  6247.0 1553.73
#Mann=8,-1,0
  4673.7    0.07       0  4706.2    0.16       0  4910.5    0.07       0
  4914.3    0.16       0  5034.3    0.07       0  5187.7    0.07       0
  5238.3    0.07       0  5510.1   0.035       0
Bank Sta=5187.7,5238.3
Exp/Cntr=0.3,0.1

Type RM Length L Ch R = 1,3501,1017,1017,1017
BEGIN DESCRIPTION:
Mapping XS 376c4579
END DESCRIPTION:
XS GIS Cut Line= 3
      1625592.01      6957459.16      1625348.94      6958544.27
      1625019.08      6960870.70
#Sta/Elev= 30
  3894.5 1582.41  4045.1 1575.11  4356.4 1570.07  4461.3 1568.34  4620.7 1565.15
  4649.3 1564.05  4820.5 1555.47  4837.8 1552.12  4911.6 1541.39  4973.0 1524.51
  4974.0 1524.01  5023.7 1524.51  5060.8 1525.46  5091.1 1537.71  5151.7 1528.53
  5202.2 1534.25  5252.7 1528.39  5351.0 1531.63  5384.1 1531.52  5429.2 1535.66
  5454.7 1542.99  5505.2 1533.43  5545.6 1541.80  5606.2 1538.06  5747.6 1546.10
  6585.9 1553.98  6630.6 1551.09  6769.3 1552.65  6838.5 1554.69  7356.2 1568.53
#Mann=17,-1,0
  3894.5   0.035       0  4045.1    0.07       0  4356.4   0.035       0
  4461.3    0.07       0  4620.7   0.035       0  4649.3    0.07       0
  4820.5   0.035       0  4837.8    0.07       0  4973.0    0.07       0
  5023.7    0.07       0  5351.0   0.035       0  5384.1    0.07       0
  5429.2   0.035       0  6585.9    0.07       0  6630.6   0.035       0
  6769.3    0.07       0  6838.5   0.035       0
Bank Sta=4973,5023.7
Exp/Cntr=0.3,0.1

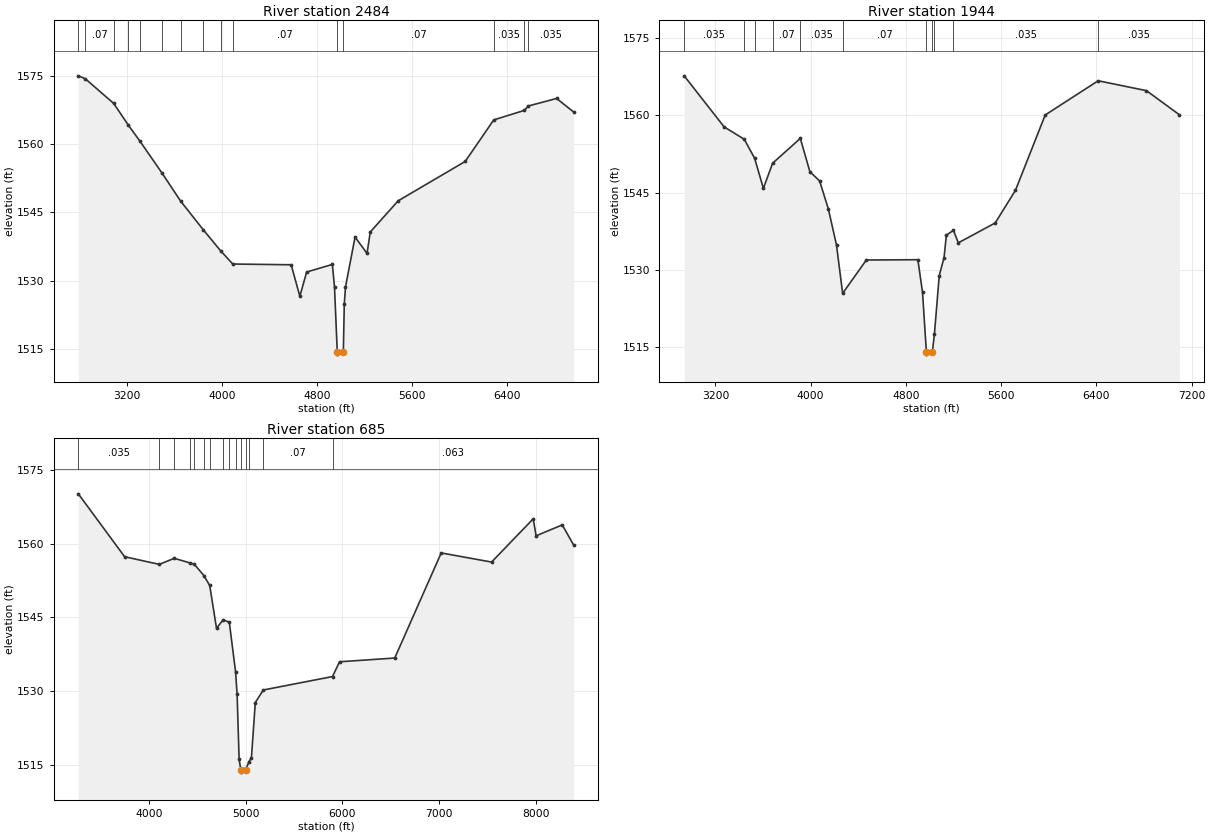
Type RM Length L Ch R = 1,2484,540,540,540
BEGIN DESCRIPTION:
Mapping XS 52bde628
END DESCRIPTION:
XS GIS Cut Line= 3
      1625080.15      6956768.77      1624459.52      6958888.06
      1624697.49      6960833.36
#Sta/Elev= 30
  2791.7 1574.94  2851.4 1574.28  3089.8 1568.88  3209.5 1564.24  3310.4 1560.60
  3495.0 1553.65  3653.4 1547.43  3844.3 1541.13  3990.3 1536.52  4091.5 1533.64
  4583.1 1533.48  4656.1 1526.57  4713.5 1531.89  4929.7 1533.55  4947.8 1528.62
  4971.0 1514.37  4972.0 1513.87  5022.1 1514.37  5030.2 1524.89  5040.2 1528.58
  5120.8 1539.56  5221.6 1535.97  5248.9 1540.67  5483.5 1547.51  6047.7 1556.15
  6288.1 1565.27  6546.1 1567.36  6579.8 1568.33  6817.1 1569.97  6959.8 1567.02
#Mann=15,-1,0
  2791.7   0.035       0  2851.4    0.07       0  3089.8   0.035       0
  3209.5    0.07       0  3310.4   0.035       0  3495.0    0.07       0
  3653.4   0.035       0  3844.3    0.07       0  3990.3   0.035       0
  4091.5    0.07       0  4971.0    0.07       0  5022.1    0.07       0
  6288.1   0.035       0  6546.1    0.07       0  6579.8   0.035       0
Bank Sta=4971,5022.1
Exp/Cntr=0.3,0.1

Type RM Length L Ch R = 1,1944,1259,1259,1259
BEGIN DESCRIPTION:
Mapping XS 71cbcd14
END DESCRIPTION:
XS GIS Cut Line= 3
      1624875.00      6956813.34      1623994.47      6958677.99
      1623994.78      6960774.99
#Sta/Elev= 30
  2937.9 1567.70  3273.4 1557.79  3442.9 1555.37  3529.8 1551.68  3603.2 1545.84
  3680.6 1550.72  3913.4 1555.55  3993.7 1549.08  4075.2 1547.29  4149.0 1541.84
  4217.3 1534.81  4268.8 1525.45  4467.7 1531.93  4900.5 1531.99  4939.7 1525.63
  4971.7 1514.15  4972.7 1513.65  5022.8 1514.15  5039.6 1517.57  5080.0 1528.90
  5120.0 1532.35  5140.0 1536.77  5199.6 1537.69  5240.0 1535.26  5550.0 1539.13
  5720.0 1545.46  5970.0 1560.10  6414.6 1566.74  6820.0 1564.82  7097.0 1560.13
#Mann=11,-1,0
  2937.9   0.035       0  3442.9    0.07       0  3529.8   0.035       0
  3680.6    0.07       0  3913.4   0.035       0  4268.8    0.07       0
  4971.7    0.07       0  5022.8    0.07       0  5039.6   0.063       0
  5199.6   0.035       0  6414.6   0.035       0
Bank Sta=4971.7,5022.8
Exp/Cntr=0.3,0.1

Type RM Length L Ch R = 1,685,0,0,0
BEGIN DESCRIPTION:
Mapping XS 21c9e230
END DESCRIPTION:
XS GIS Cut Line= 3
      1624863.16      6956561.02      1623550.45      6957687.98
      1623722.48      6961074.82
#Sta/Elev= 30
  3269.9 1570.17  3748.7 1557.36  4107.4 1555.80  4262.3 1557.03  4421.0 1556.12
  4469.8 1555.82  4567.7 1553.53  4628.8 1551.50  4699.1 1542.78  4768.0 1544.52
  4831.6 1543.99  4896.2 1533.88  4912.0 1529.31  4932.8 1516.09  4950.0 1513.98
  4951.0 1513.48  5001.3 1513.98  5034.6 1515.62  5060.1 1516.41  5100.1 1527.66
  5183.1 1530.21  5898.6 1532.95  5971.3 1535.96  6542.0 1536.72  7022.6 1558.13
  7543.3 1556.27  7973.8 1565.08  8003.9 1561.62  8274.2 1563.84  8391.2 1559.76
#Mann=15,-1,0
  3269.9   0.035       0  4107.4   0.045       0  4262.3   0.035       0
  4421.0    0.07       0  4469.8   0.035       0  4567.7    0.07       0
  4628.8    0.16       0  4768.0    0.07       0  4831.6    0.16       0
  4896.2    0.07       0  4950.0    0.07       0  5001.3    0.07       0
  5034.6    0.16       0  5183.1    0.07       0  5898.6   0.063       0
Bank Sta=4950,5001.3
Exp/Cntr=0.3,0.1

Chan Stop Cuts=-1