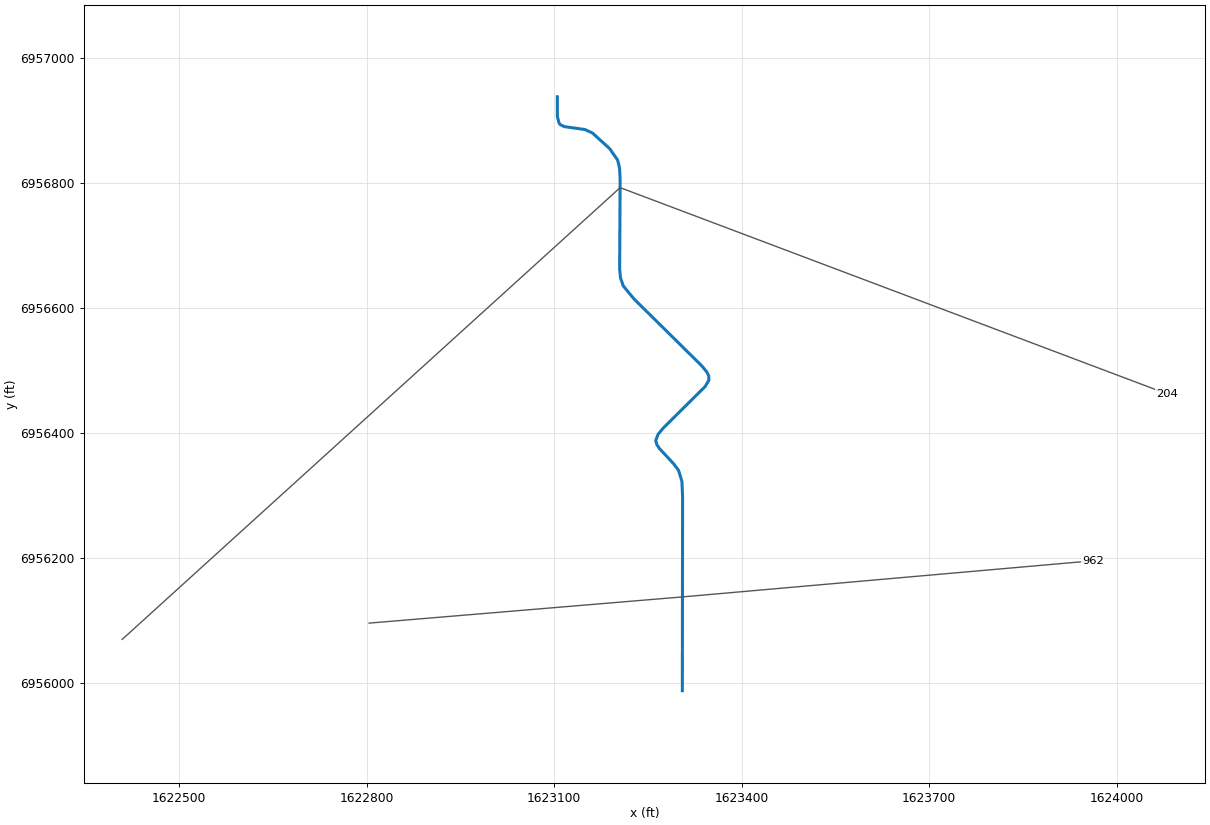
--- Chimney Creek 1096.prj (project) ---

Proj Title=Chimney Creek 1096 Base Level Engineering
Current Plan=p01
Default Exp/Contr=0.3,0.1
English Units
Geom File=g01
Flow File=f01
Plan File=p01
BEGIN DESCRIPTION:
Chimney Creek 1096
END DESCRIPTION:

--- Chimney Creek 1096.p01 (plan) ---

Plan Title=Multiple Run
Short Identifier=Multiple
Geom File=g01
Flow File=f01
Subcritical Flow
K Sum by GR= 0
Std Step Tol= 0.01
Critical Tol= 0.01
Num of Std Step Trials= 20
Max Error Tol= 0.3
Flow Tol Ratio= 0.001
Split Flow NTrial= 30
Split Flow Tol= 0.02
Split Flow Ratio= 0.02
Log Output Level= 0
Friction Slope Method= 1
Unsteady Friction Slope Method= 2
Unsteady Bridges Friction Slope Method= 1
Parabolic Critical Depth
Global Vel Dist=  1 , 1 , 1
Global Log Level= 0
CheckData=True
Encroach Param= -1, 0, 0, 0
BEGIN DESCRIPTION:
Multiple Run
END DESCRIPTION:

--- Chimney Creek 1096.f01 (steady flow) ---

Flow Title=Multiple
Number of Profiles=7
Profile Names=10-year,25-year,50-year,1pct_min,100-year,1pct_plu,500-year
River Rch & RM= Chimney Creek 10,Reach-1,962
     211     289     351     213     425     849     631
Boundary for River Rch & Prof#=Chimney Creek 10,Reach-1,1
Up Type=0
Dn Type=3
Dn Slope=0.005
Boundary for River Rch & Prof#=Chimney Creek 10,Reach-1,2
Up Type=0
Dn Type=3
Dn Slope=0.005
Boundary for River Rch & Prof#=Chimney Creek 10,Reach-1,3
Up Type=0
Dn Type=3
Dn Slope=0.005
Boundary for River Rch & Prof#=Chimney Creek 10,Reach-1,4
Up Type=0
Dn Type=3
Dn Slope=0.005
Boundary for River Rch & Prof#=Chimney Creek 10,Reach-1,5
Up Type=0
Dn Type=3
Dn Slope=0.005
Boundary for River Rch & Prof#=Chimney Creek 10,Reach-1,6
Up Type=0
Dn Type=3
Dn Slope=0.005
Boundary for River Rch & Prof#=Chimney Creek 10,Reach-1,7
Up Type=0
Dn Type=3
Dn Slope=0.005

--- Chimney Creek 1096.g01 (geometry) ---

Geom Title=Existing Conditions

River Reach=Chimney Creek 10,Reach-1
Reach XY= 30
      1623305.00      6955988.00      1623305.40      6956298.21
      1623304.34      6956322.84      1623298.97      6956340.45
      1623290.78      6956351.32      1623268.84      6956374.84
      1623264.30      6956381.47      1623262.34      6956388.10
      1623266.14      6956398.06      1623274.38      6956408.03
      1623341.54      6956474.67      1623347.38      6956484.67
      1623347.39      6956491.33      1623344.04      6956498.00
      1623335.78      6956508.00      1623227.86      6956614.47
      1623210.46      6956635.55      1623206.05      6956648.43
      1623204.71      6956662.88      1623205.48      6956806.43
      1623204.51      6956824.27      1623201.55      6956836.75
      1623188.71      6956855.14      1623161.27      6956880.09
      1623149.04      6956885.80      1623116.83      6956890.25
      1623109.96      6956893.35      1623107.66      6956896.45
      1623105.09      6956906.47      1623105.00      6956938.00

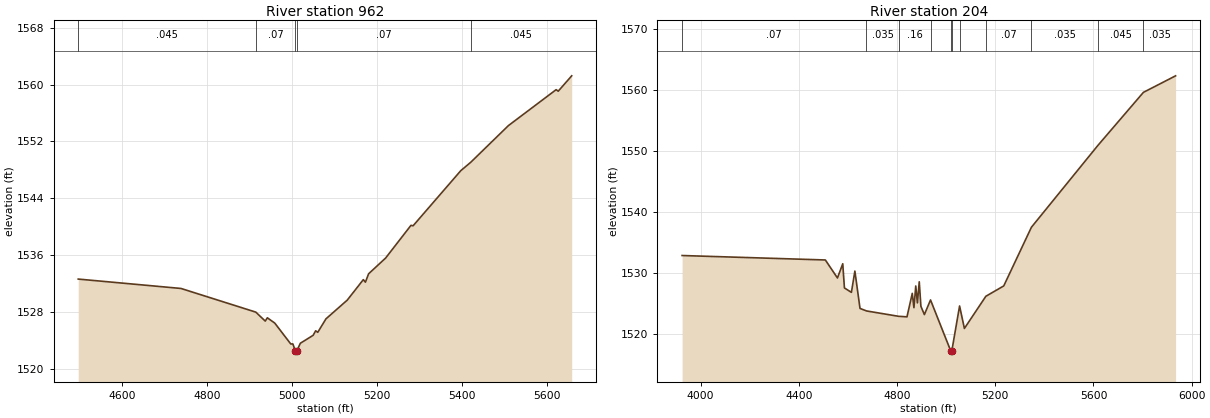
Type RM Length L Ch R = 1,962,758,758,758
BEGIN DESCRIPTION:
Chimney Creek 1096 2.0
END DESCRIPTION:
XS GIS Cut Line= 3
      1622803.87      6956096.09      1623305.00      6956138.00
      1623961.38      6956195.80
#Sta/Elev= 30
  4497.1 1532.64  4739.1 1531.32  4915.2 1527.99  4937.4 1526.73  4942.4 1527.19
  4959.8 1526.45  4997.5 1523.51  5002.5 1523.51  5008.0 1522.58  5008.3 1522.08
  5011.8 1522.08  5012.0 1522.58  5020.1 1523.61  5050.2 1524.73  5056.1 1525.36
  5061.1 1525.15  5080.3 1527.04  5130.5 1529.68  5168.3 1532.56  5173.3 1532.21
  5180.7 1533.38  5220.8 1535.60  5280.5 1540.20  5285.5 1540.14  5397.7 1547.89
  5421.3 1549.08  5510.0 1554.24  5622.2 1559.29  5627.2 1559.08  5658.9 1561.24
#Mann=5,-1,0
  4497.1   0.045       0  4915.2    0.07       0  5008.0    0.07       0
  5012.0    0.07       0  5421.3   0.045       0
Bank Sta=5008,5012
Exp/Cntr=0.3,0.1

Type RM Length L Ch R = 1,204,0,0,0
BEGIN DESCRIPTION:
Chimney Creek 1096 1.0
END DESCRIPTION:
XS GIS Cut Line= 3
      1622408.88      6956070.04      1623205.48      6956792.77
      1624079.97      6956463.01
#Sta/Elev= 30
  3924.4 1532.84  4507.9 1532.11  4557.2 1529.16  4578.8 1531.49  4585.6 1527.53
  4614.0 1526.80  4628.2 1530.29  4649.1 1524.17  4675.4 1523.76  4805.9 1522.88
  4840.4 1522.79  4862.0 1526.64  4868.7 1524.29  4876.2 1527.85  4882.9 1525.08
  4890.4 1528.54  4897.1 1524.52  4911.3 1523.16  4936.3 1525.56  5018.9 1517.18
  5019.1 1516.68  5022.9 1517.18  5054.7 1524.57  5074.3 1520.89  5161.7 1526.16
  5234.6 1527.86  5347.4 1537.48  5617.8 1550.87  5803.5 1559.58  5934.6 1562.29
#Mann=11,-1,0
  3924.4    0.07       0  4675.4   0.035       0  4805.9    0.16       0
  4936.3    0.07       0  5018.9    0.07       0  5022.9    0.07       0
  5054.7    0.16       0  5161.7    0.07       0  5347.4   0.035       0
  5617.8   0.045       0  5803.5   0.035       0
Bank Sta=5018.9,5022.9
Exp/Cntr=0.3,0.1

Chan Stop Cuts=-1