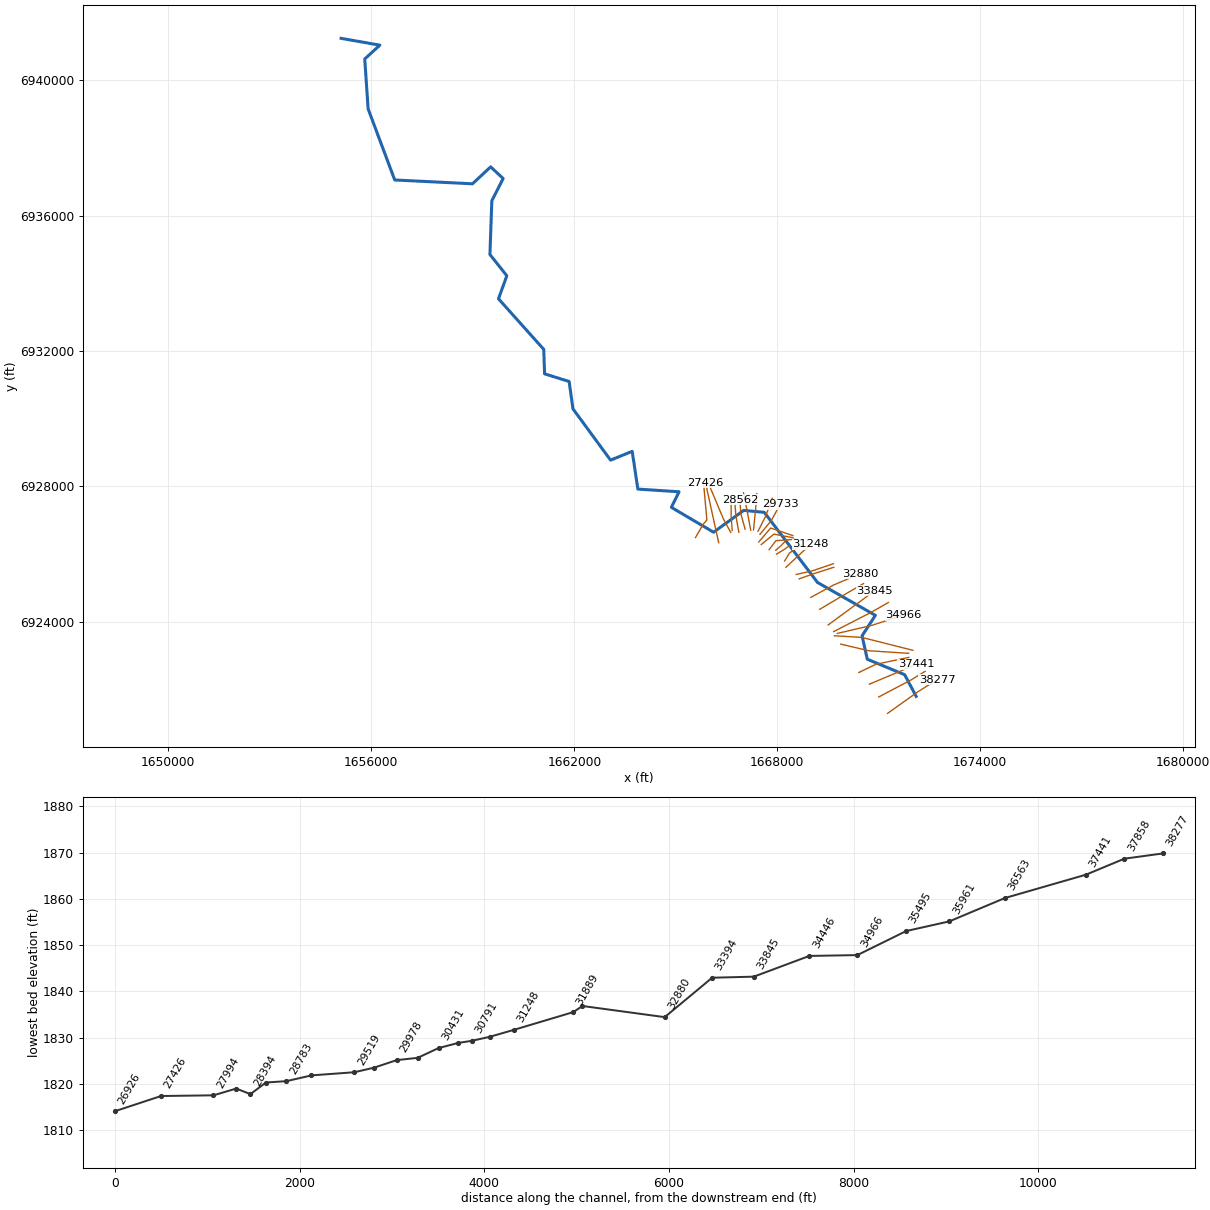
--- Chimney Creek 1097.prj (project) ---

Proj Title=Chimney Creek 1097 Base Level Engineering
Current Plan=p01
Default Exp/Contr=0.3,0.1
English Units
Geom File=g01
Flow File=f01
Plan File=p01
BEGIN DESCRIPTION:
Chimney Creek 1097
END DESCRIPTION:

--- Chimney Creek 1097.p01 (plan) ---

Plan Title=Multiple Run
Short Identifier=Multiple
Geom File=g01
Flow File=f01
Subcritical Flow
K Sum by GR= 0
Std Step Tol= 0.01
Critical Tol= 0.01
Num of Std Step Trials= 20
Max Error Tol= 0.3
Flow Tol Ratio= 0.001
Split Flow NTrial= 30
Split Flow Tol= 0.02
Split Flow Ratio= 0.02
Log Output Level= 0
Friction Slope Method= 1
Unsteady Friction Slope Method= 2
Unsteady Bridges Friction Slope Method= 1
Parabolic Critical Depth
Global Vel Dist=  1 , 1 , 1
Global Log Level= 0
CheckData=True
Encroach Param= -1, 0, 0, 0
BEGIN DESCRIPTION:
Multiple Run
END DESCRIPTION:

--- Chimney Creek 1097.f01 (steady flow) ---

Flow Title=Multiple
Number of Profiles=7
Profile Names=10-year,25-year,50-year,1pct_min,100-year,1pct_plu,500-year
River Rch & RM= Chimney Creek 10,Reach-1,38277
     222     303     369     224     448     894     666
River Rch & RM= Chimney Creek 10,Reach-1,37858
     349     489     606     374     745    1487    1142
River Rch & RM= Chimney Creek 10,Reach-1,29733
     589     846    1066     667    1330    2654    2100
River Rch & RM= Chimney Creek 10,Reach-1,22793
     669     964    1216     762    1519    3032    2405
River Rch & RM= Chimney Creek 10,Reach-1,10960
    1056    1552    1985    1258    2511    5010    4073
River Rch & RM= Chimney Creek 10,Reach-1,5830
    1074    1576    2015    1277    2547    5083    4127
River Rch & RM= Chimney Creek 10,Reach-1,1176
    1164    1713    2192    1391    2774    5536    4504
Boundary for River Rch & Prof#=Chimney Creek 10,Reach-1,1
Up Type=0
Dn Type=3
Dn Slope=0.0005
Boundary for River Rch & Prof#=Chimney Creek 10,Reach-1,2
Up Type=0
Dn Type=3
Dn Slope=0.0005
Boundary for River Rch & Prof#=Chimney Creek 10,Reach-1,3
Up Type=0
Dn Type=3
Dn Slope=0.0005
Boundary for River Rch & Prof#=Chimney Creek 10,Reach-1,4
Up Type=0
Dn Type=3
Dn Slope=0.0005
Boundary for River Rch & Prof#=Chimney Creek 10,Reach-1,5
Up Type=0
Dn Type=3
Dn Slope=0.0005
Boundary for River Rch & Prof#=Chimney Creek 10,Reach-1,6
Up Type=0
Dn Type=3
Dn Slope=0.0005
Boundary for River Rch & Prof#=Chimney Creek 10,Reach-1,7
Up Type=0
Dn Type=3
Dn Slope=0.0005

--- Chimney Creek 1097.g01 (geometry) ---

Geom Title=Existing Conditions

River Reach=Chimney Creek 10,Reach-1
Reach XY= 30
      1672105.00      6921788.00      1671764.68      6922427.22
      1670660.28      6922885.29      1670506.20      6923577.49
      1670899.44      6924182.38      1669188.29      6925154.63
      1667615.39      6927227.22      1667006.47      6927284.46
      1666116.83      6926639.61      1664868.35      6927374.66
      1665096.70      6927834.93      1663878.06      6927914.12
      1663711.06      6929029.86      1663071.39      6928770.36
      1661960.83      6930285.70      1661847.19      6931094.19
      1661121.29      6931321.29      1661096.87      6932044.08
      1659758.54      6933539.46      1660004.93      6934219.77
      1659505.93      6934848.48      1659562.08      6936438.00
      1659896.88      6937094.05      1659527.80      6937438.56
      1658989.84      6936938.39      1656691.68      6937051.37
      1655905.51      6939153.21      1655805.74      6940627.85
      1656251.91      6941036.37      1655105.00      6941238.00

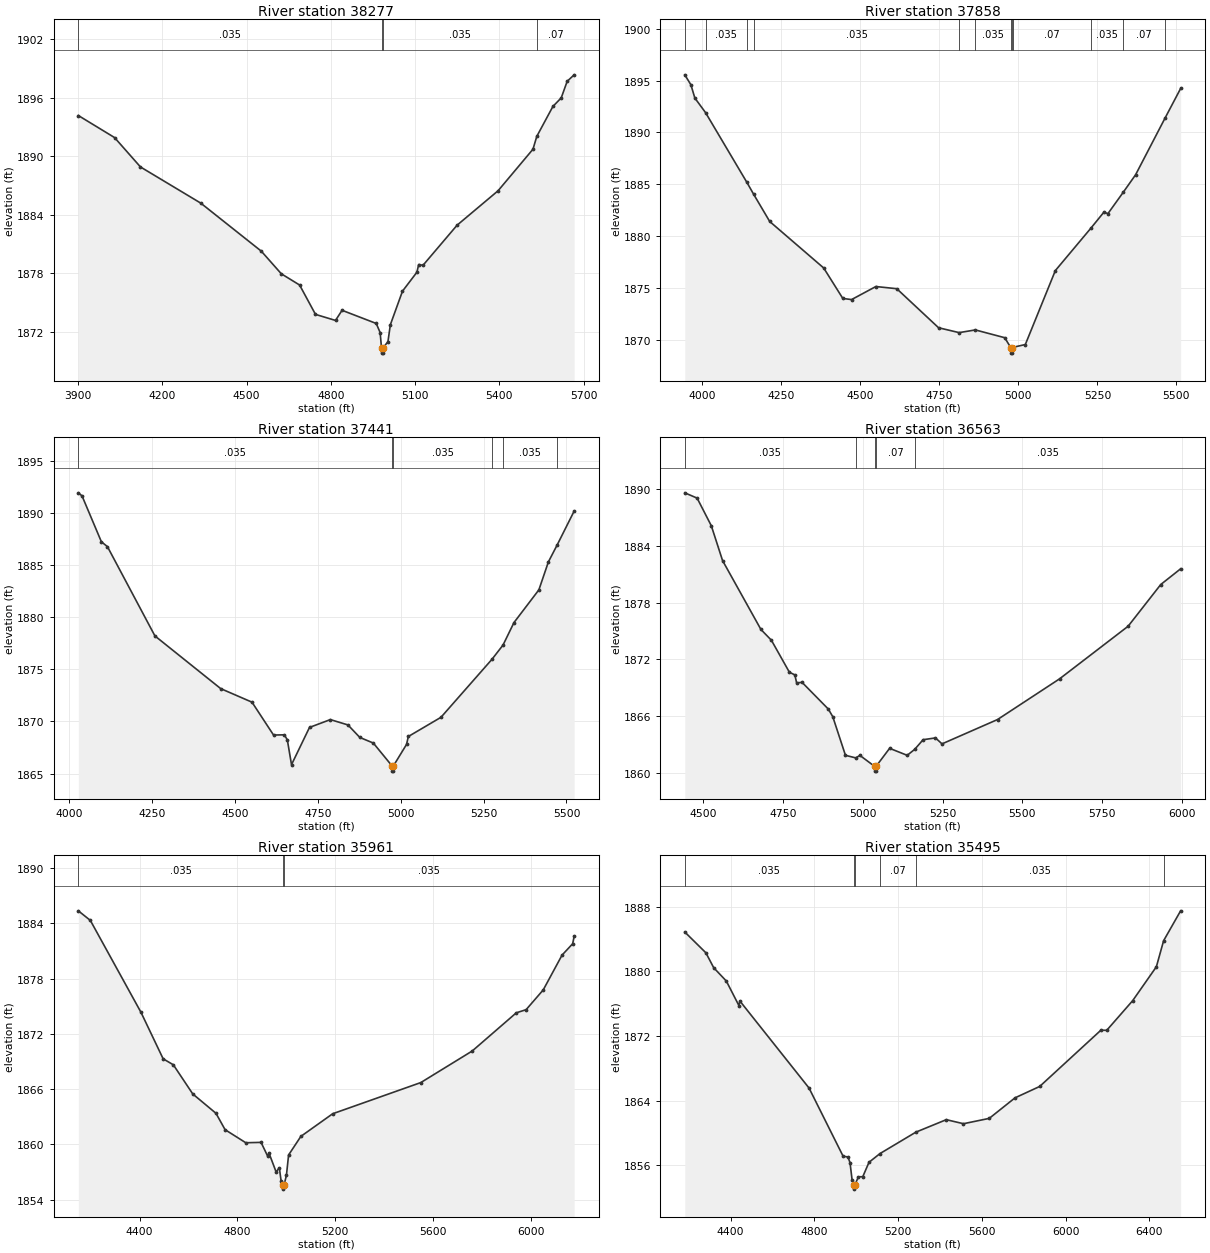
Type RM Length L Ch R = 1,38277,419,419,419
BEGIN DESCRIPTION:
Chimney Creek 1097 63.0
END DESCRIPTION:
XS GIS Cut Line= 3
      1671259.84      6921284.66      1672154.97      6921922.62
      1672719.12      6922277.33
#Sta/Elev= 30
  3900.8 1894.18  4029.8 1891.92  4122.0 1888.91  4336.9 1885.20  4552.3 1880.28
  4623.6 1877.96  4688.7 1876.81  4745.3 1873.80  4816.6 1873.18  4839.9 1874.22
  4961.6 1872.87  4975.5 1871.94  4980.5 1870.33  4980.8 1869.83  4984.3 1869.83
  4984.5 1870.33  5003.3 1871.00  5011.9 1872.74  5055.1 1876.18  5106.4 1878.12
  5112.8 1878.91  5128.1 1878.83  5249.5 1882.94  5395.5 1886.47  5519.8 1890.73
  5533.3 1892.04  5590.7 1895.11  5620.4 1895.99  5641.6 1897.69  5666.4 1898.35
#Mann=4,-1,0
  3900.8   0.035       0  4980.5   0.035       0  4984.5   0.035       0
  5533.3    0.07       0
Bank Sta=4980.5,4984.5
Exp/Cntr=0.3,0.1

Type RM Length L Ch R = 1,37858,417,417,417
BEGIN DESCRIPTION:
Mapping XS cffcd6df
END DESCRIPTION:
XS GIS Cut Line= 3
      1670997.93      6921770.29      1671935.40      6922262.46
      1672371.42      6922527.19
#Sta/Elev= 30
  3944.5 1895.56  3963.8 1894.60  3976.3 1893.32  4010.2 1891.91  4140.5 1885.20
  4162.7 1884.01  4213.2 1881.40  4384.0 1876.91  4444.5 1873.97  4472.2 1873.86
  4549.1 1875.12  4615.2 1874.91  4747.5 1871.14  4812.5 1870.67  4863.9 1870.93
  4956.7 1870.18  4976.7 1869.19  4977.0 1868.69  4980.6 1868.69  4980.8 1869.19
  4982.5 1869.25  5022.0 1869.52  5117.0 1876.66  5229.6 1880.76  5270.1 1882.28
  5283.6 1882.17  5331.6 1884.21  5370.9 1885.91  5464.9 1891.43  5513.4 1894.24
#Mann=12,-1,0
  3944.5    0.07       0  4010.2   0.035       0  4140.5    0.07       0
  4162.7   0.035       0  4812.5    0.07       0  4863.9   0.035       0
  4976.7    0.07       0  4980.8   0.035       0  4982.5    0.07       0
  5229.6   0.035       0  5331.6    0.07       0  5464.9   0.035       0
Bank Sta=4976.7,4980.8
Exp/Cntr=0.3,0.1

Type RM Length L Ch R = 1,37441,878,878,878
BEGIN DESCRIPTION:
Mapping XS 1eadc839
END DESCRIPTION:
XS GIS Cut Line= 3
      1670721.84      6922147.87      1671622.90      6922525.49
      1672096.89      6922736.44
#Sta/Elev= 30
  4027.4 1891.91  4038.5 1891.62  4096.9 1887.22  4115.2 1886.75  4258.5 1878.19
  4456.9 1873.14  4551.3 1871.84  4616.3 1868.69  4648.9 1868.71  4657.9 1868.23
  4670.5 1865.85  4724.8 1869.42  4787.7 1870.17  4840.7 1869.66  4876.6 1868.46
  4917.4 1867.92  4973.8 1865.73  4974.0 1865.23  4977.6 1865.23  4977.9 1865.73
  5017.5 1867.79  5023.0 1868.55  5121.4 1870.39  5275.5 1875.96  5308.7 1877.32
  5341.6 1879.47  5416.8 1882.61  5445.5 1885.29  5471.9 1886.91  5523.2 1890.16
#Mann=6,-1,0
  4027.4   0.035       0  4973.8   0.035       0  4977.9   0.035       0
  5275.5    0.07       0  5308.7   0.035       0  5471.9    0.07       0
Bank Sta=4973.8,4977.9
Exp/Cntr=0.3,0.1

Type RM Length L Ch R = 1,36563,602,602,602
BEGIN DESCRIPTION:
Mapping XS 85fef3d3
END DESCRIPTION:
XS GIS Cut Line= 3
      1670410.21      6922493.36      1670911.96      6922734.69
      1671885.88      6922939.54
#Sta/Elev= 30
  4443.3 1889.59  4481.9 1889.03  4526.3 1886.11  4561.5 1882.43  4681.6 1875.15
  4714.4 1874.01  4770.7 1870.63  4787.8 1870.35  4793.3 1869.51  4810.4 1869.56
  4892.5 1866.74  4906.5 1865.93  4946.2 1861.85  4978.3 1861.58  4991.5 1861.84
  5037.6 1860.68  5037.9 1860.18  5041.6 1860.18  5041.9 1860.68  5084.4 1862.59
  5139.4 1861.85  5162.9 1862.48  5189.2 1863.50  5228.0 1863.69  5248.4 1863.06
  5422.1 1865.63  5616.3 1869.93  5830.9 1875.49  5933.1 1879.90  5995.3 1881.56
#Mann=5,-1,0
  4443.3   0.035       0  4978.3    0.07       0  5037.6    0.07       0
  5041.9    0.07       0  5162.9   0.035       0
Bank Sta=5037.6,5041.9
Exp/Cntr=0.3,0.1

Type RM Length L Ch R = 1,35961,466,466,466
BEGIN DESCRIPTION:
Mapping XS e8dddab6
END DESCRIPTION:
XS GIS Cut Line= 3
      1669877.17      6923331.12      1670706.15      6923135.81
      1671881.22      6923059.93
#Sta/Elev= 30
  4149.0 1885.37  4198.1 1884.33  4405.6 1874.33  4496.1 1869.29  4537.8 1868.64
  4617.4 1865.47  4712.3 1863.37  4749.6 1861.59  4834.3 1860.17  4896.8 1860.21
  4924.1 1858.70  4929.2 1859.05  4958.4 1857.00  4971.6 1857.45  4979.0 1855.99
  4987.0 1855.63  4987.3 1855.13  4991.4 1855.63  5000.7 1856.64  5009.5 1858.84
  5059.7 1860.86  5189.9 1863.32  5550.7 1866.71  5761.1 1870.14  5941.5 1874.29
  5981.6 1874.63  6051.7 1876.78  6128.7 1880.56  6172.0 1881.79  6178.2 1882.59
#Mann=3,-1,0
  4149.0   0.035       0  4987.0   0.035       0  4991.4   0.035       0
Bank Sta=4987,4991.4
Exp/Cntr=0.3,0.1

Type RM Length L Ch R = 1,35495,529,529,529
BEGIN DESCRIPTION:
Mapping XS d9821020
END DESCRIPTION:
XS GIS Cut Line= 3
      1669687.05      6923578.96      1670502.15      6923529.48
      1672007.37      6923149.27
#Sta/Elev= 30
  4180.9 1884.85  4281.6 1882.28  4319.1 1880.43  4379.2 1878.79  4439.3 1875.76
  4444.3 1876.31  4774.6 1865.55  4937.3 1857.12  4960.3 1857.03  4970.3 1856.33
  4980.3 1854.18  4988.1 1853.55  4988.4 1853.05  4992.6 1853.55  5010.8 1854.57
  5031.4 1854.59  5061.0 1856.37  5113.7 1857.45  5285.2 1860.10  5430.4 1861.64
  5512.5 1861.14  5635.6 1861.80  5758.7 1864.34  5876.7 1865.75  6169.2 1872.71
  6196.9 1872.69  6320.6 1876.35  6434.1 1880.55  6468.8 1883.78  6550.0 1887.47
#Mann=6,-1,0
  4180.9   0.035       0  4988.1   0.035       0  4992.6   0.035       0
  5113.7    0.07       0  5285.2   0.035       0  6468.8    0.07       0
Bank Sta=4988.1,4992.6
Exp/Cntr=0.3,0.1

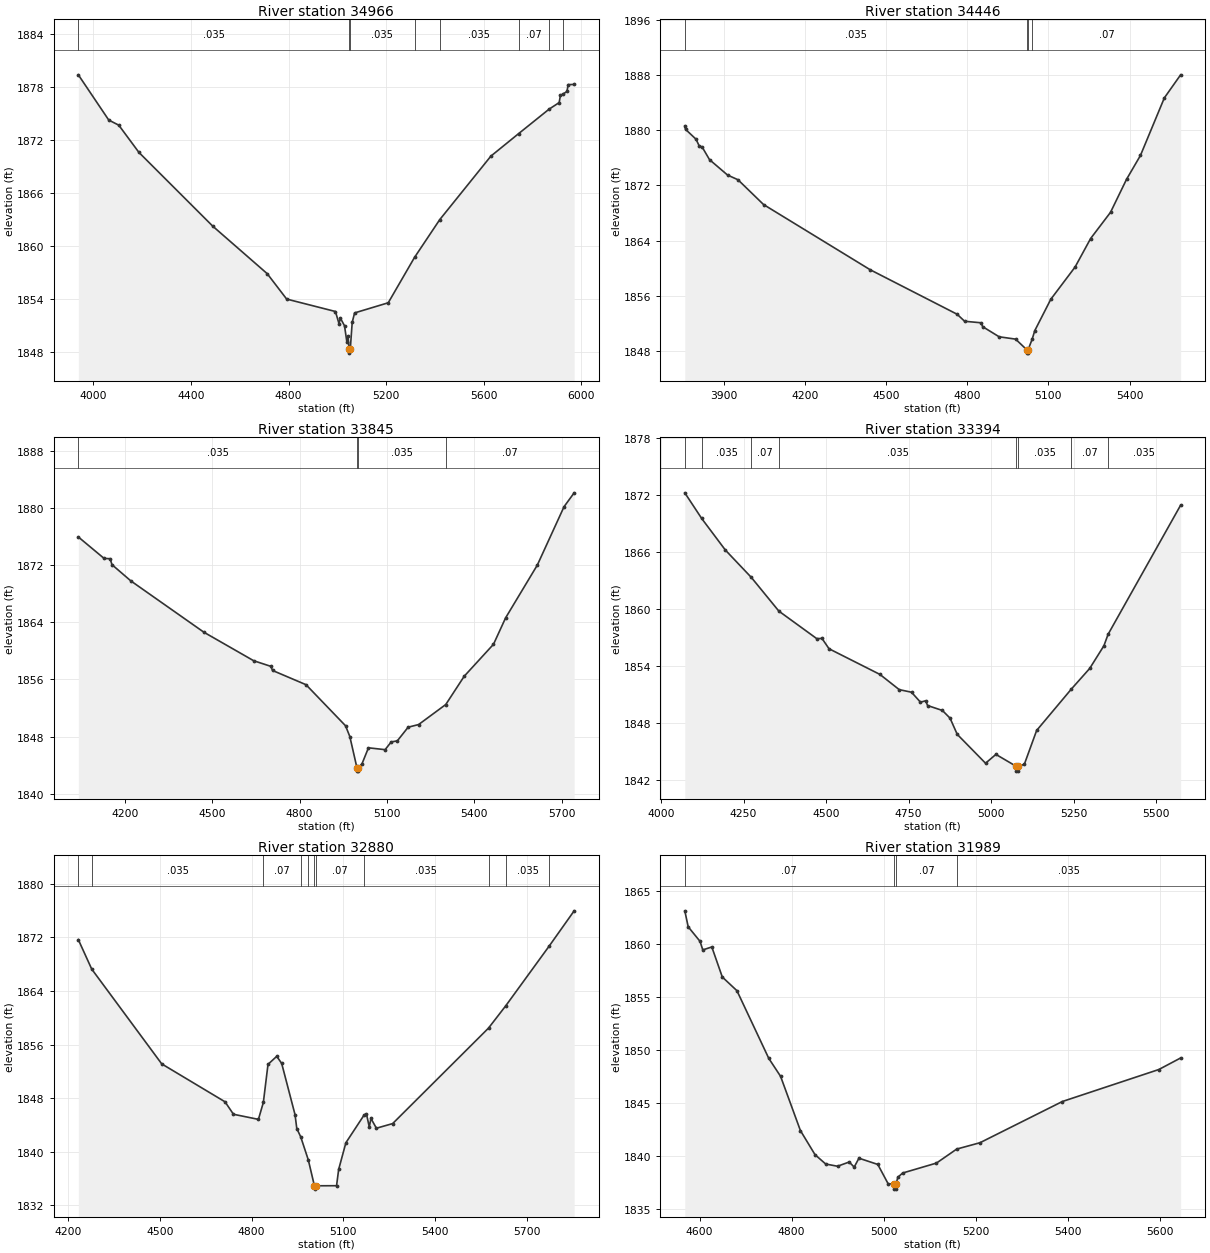
Type RM Length L Ch R = 1,34966,520,520,520
BEGIN DESCRIPTION:
Mapping XS 79419c79
END DESCRIPTION:
XS GIS Cut Line= 3
      1669773.59      6923647.57      1670799.68      6923887.16
      1671729.34      6924191.84
#Sta/Elev= 30
  3938.3 1879.41  4063.0 1874.28  4104.1 1873.70  4186.7 1870.61  4489.5 1862.24
  4712.4 1856.86  4792.1 1853.98  4992.0 1852.57  5006.8 1851.17  5012.1 1851.83
  5029.2 1850.95  5038.6 1849.16  5043.9 1849.77  5047.6 1848.35  5048.0 1847.85
  5052.9 1848.35  5060.7 1851.34  5070.5 1852.41  5208.4 1853.56  5316.2 1858.71
  5419.5 1862.99  5629.0 1870.19  5742.6 1872.74  5867.7 1875.52  5908.8 1876.26
  5914.1 1877.08  5925.5 1877.25  5940.7 1877.52  5945.9 1878.30  5970.3 1878.32
#Mann=8,-1,0
  3938.3   0.035       0  5047.6   0.035       0  5052.9   0.035       0
  5316.2    0.07       0  5419.5   0.035       0  5742.6    0.07       0
  5867.7   0.035       0  5925.5    0.07       0
Bank Sta=5047.6,5052.9
Exp/Cntr=0.3,0.1

Type RM Length L Ch R = 1,34446,601,601,601
BEGIN DESCRIPTION:
Mapping XS 5b3147fd
END DESCRIPTION:
XS GIS Cut Line= 3
      1669666.86      6923702.26      1670771.03      6924269.97
      1671284.05      6924561.63
#Sta/Elev= 30
  3757.0 1880.64  3759.6 1880.13  3798.3 1878.70  3811.1 1877.65  3820.5 1877.60
  3848.3 1875.73  3914.8 1873.50  3953.6 1872.81  4047.9 1869.22  4441.5 1859.77
  4763.0 1853.31  4790.8 1852.29  4851.7 1852.07  4857.3 1851.51  4918.2 1850.04
  4979.1 1849.70  5020.0 1848.17  5020.4 1847.67  5024.9 1847.67  5025.3 1848.17
  5040.0 1849.66  5050.0 1850.94  5109.1 1855.48  5198.7 1860.15  5256.2 1864.29
  5329.7 1868.09  5388.8 1872.87  5440.3 1876.34  5528.6 1884.69  5588.7 1888.03
#Mann=4,-1,0
  3757.0   0.035       0  5020.0   0.035       0  5025.3   0.035       0
  5040.0    0.07       0
Bank Sta=5020,5025.3
Exp/Cntr=0.3,0.1

Type RM Length L Ch R = 1,33845,451,451,451
BEGIN DESCRIPTION:
Mapping XS f325fc53
END DESCRIPTION:
XS GIS Cut Line= 3
      1669502.78      6923897.56      1670284.05      6924473.10
      1670875.19      6924905.38
#Sta/Elev= 30
  4039.9 1875.92  4128.4 1872.92  4149.2 1872.88  4155.4 1872.05  4220.2 1869.78
  4470.9 1862.61  4642.1 1858.62  4700.7 1857.84  4706.9 1857.26  4821.8 1855.27
  4957.5 1849.53  4972.2 1848.03  4996.5 1843.69  4997.0 1843.19  5001.5 1843.19
  5001.9 1843.69  5014.0 1844.21  5036.2 1846.45  5093.4 1846.19  5114.3 1847.27
  5135.3 1847.42  5172.5 1849.33  5208.4 1849.70  5301.7 1852.50  5365.2 1856.46
  5465.6 1860.92  5507.3 1864.62  5616.1 1871.99  5708.0 1880.16  5742.6 1882.09
#Mann=4,-1,0
  4039.9   0.035       0  4996.5   0.035       0  5001.9   0.035       0
  5301.7    0.07       0
Bank Sta=4996.5,5001.9
Exp/Cntr=0.3,0.1

Type RM Length L Ch R = 1,33394,514,514,514
BEGIN DESCRIPTION:
Mapping XS 11606225
END DESCRIPTION:
XS GIS Cut Line= 3
      1669253.21      6924361.10      1670054.02      6924834.21
      1670548.85      6925120.69
#Sta/Elev= 30
  4071.9 1872.23  4123.1 1869.53  4194.8 1866.21  4273.5 1863.33  4356.8 1859.79
  4471.8 1856.89  4487.4 1856.92  4508.8 1855.83  4663.0 1853.13  4721.5 1851.53
  4758.6 1851.26  4785.8 1850.21  4801.5 1850.36  4807.3 1849.86  4852.2 1849.34
  4875.4 1848.53  4897.1 1846.83  4982.9 1843.79  5014.3 1844.72  5076.1 1843.46
  5076.6 1842.96  5081.2 1842.96  5081.6 1843.46  5100.4 1843.68  5137.7 1847.24
  5242.8 1851.59  5298.4 1853.76  5341.5 1856.15  5354.1 1857.35  5573.8 1870.93
#Mann=8,-1,0
  4071.9    0.07       0  4123.1   0.035       0  4273.5    0.07       0
  4356.8   0.035       0  5076.1   0.035       0  5081.6   0.035       0
  5242.8    0.07       0  5354.1   0.035       0
Bank Sta=5076.1,5081.6
Exp/Cntr=0.3,0.1

Type RM Length L Ch R = 1,32880,891,891,891
BEGIN DESCRIPTION:
Mapping XS 20ebee32
END DESCRIPTION:
XS GIS Cut Line= 3
      1668990.35      6924712.82      1669664.84      6925080.01
      1670450.24      6925412.90
#Sta/Elev= 30
  4233.6 1871.67  4277.3 1867.28  4506.2 1853.13  4713.2 1847.47  4740.8 1845.61
  4822.4 1844.85  4838.5 1847.38  4853.7 1853.06  4882.3 1854.26  4898.4 1853.20
  4942.1 1845.55  4947.8 1843.48  4960.6 1842.25  4985.5 1838.79  5005.4 1834.94
  5005.9 1834.44  5010.9 1834.94  5077.8 1834.95  5084.7 1837.38  5108.3 1841.36
  5167.6 1845.48  5175.5 1845.68  5184.8 1843.71  5190.2 1844.99  5208.1 1843.53
  5261.2 1844.22  5574.6 1858.47  5631.0 1861.80  5773.4 1870.74  5854.6 1875.97
#Mann=11,-1,0
  4233.6    0.07       0  4277.3   0.035       0  4838.5    0.07       0
  4960.6   0.035       0  4985.5    0.07       0  5005.4    0.07       0
  5010.9    0.07       0  5167.6   0.035       0  5574.6    0.07       0
  5631.0   0.035       0  5773.4    0.07       0
Bank Sta=5005.4,5010.9
Exp/Cntr=0.3,0.1

Type RM Length L Ch R = 1,31989,100,100,100
BEGIN DESCRIPTION:
Mapping XS 803b0db1
END DESCRIPTION:
XS GIS Cut Line= 3
      1668648.13      6925262.25      1669054.42      6925405.50
      1669670.13      6925602.94
#Sta/Elev= 30
  4567.8 1863.12  4575.2 1861.61  4600.9 1860.24  4606.9 1859.43  4626.5 1859.71
  4649.3 1856.87  4681.1 1855.58  4750.3 1849.19  4775.9 1847.50  4819.0 1842.38
  4850.8 1840.10  4874.0 1839.22  4899.7 1839.01  4925.0 1839.41  4935.9 1838.93
  4946.2 1839.77  4987.2 1839.18  5009.7 1837.35  5021.5 1837.35  5022.0 1836.85
  5026.7 1836.85  5027.1 1837.35  5030.7 1837.97  5041.2 1838.37  5114.7 1839.31
  5158.6 1840.63  5209.2 1841.23  5388.2 1845.12  5597.8 1848.14  5645.2 1849.23
#Mann=4,-1,0
  4567.8    0.07       0  5021.5    0.07       0  5027.1    0.07       0
  5158.6   0.035       0
Bank Sta=5021.5,5027.1
Exp/Cntr=0.3,0.1

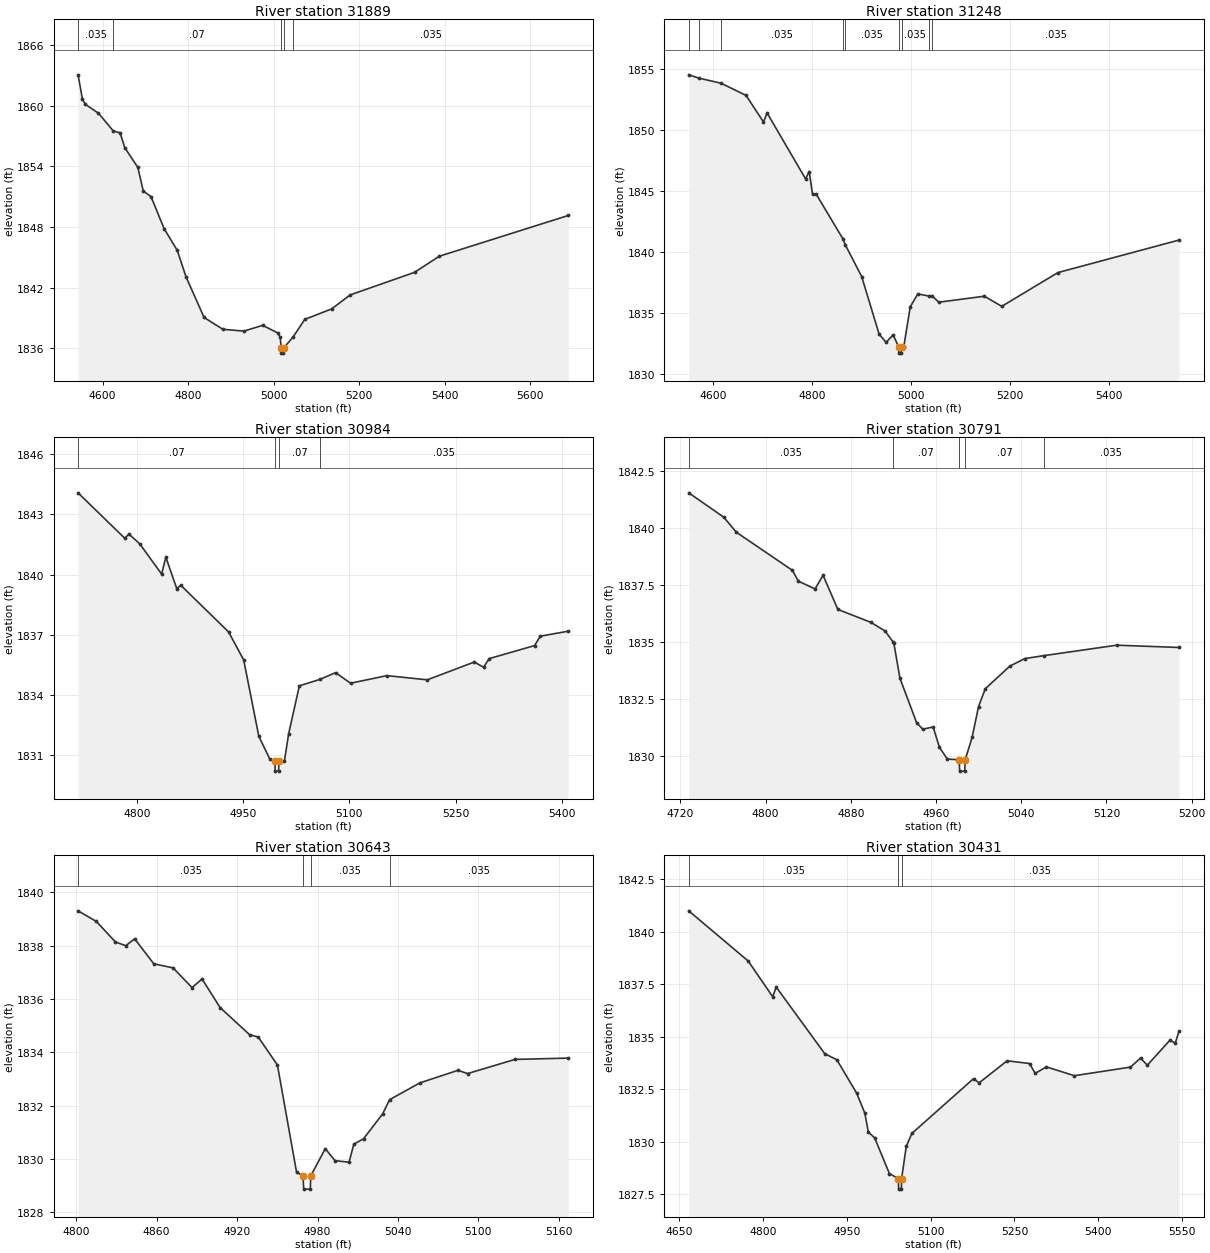
Type RM Length L Ch R = 1,31889,641,641,641
BEGIN DESCRIPTION:
Mapping XS 894aa455
END DESCRIPTION:
XS GIS Cut Line= 3
      1668558.30      6925391.17      1669007.54      6925488.83
      1669658.62      6925708.90
#Sta/Elev= 30
  4542.5 1863.07  4552.8 1860.66  4559.6 1860.15  4590.3 1859.27  4625.0 1857.51
  4640.8 1857.33  4651.7 1855.87  4682.4 1853.90  4695.0 1851.57  4713.1 1851.02
  4744.2 1847.81  4774.5 1845.70  4795.0 1843.08  4837.3 1839.05  4881.3 1837.88
  4930.4 1837.70  4974.4 1838.27  5010.0 1837.51  5015.3 1837.09  5017.9 1836.02
  5018.3 1835.52  5023.0 1835.52  5023.5 1836.02  5045.9 1837.14  5072.9 1838.86
  5135.8 1839.90  5179.0 1841.28  5329.8 1843.52  5387.4 1845.11  5689.5 1849.15
#Mann=5,-1,0
  4542.5   0.035       0  4625.0    0.07       0  5017.9    0.07       0
  5023.5    0.07       0  5045.9   0.035       0
Bank Sta=5017.9,5023.5
Exp/Cntr=0.3,0.1

Type RM Length L Ch R = 1,31248,264,264,264
BEGIN DESCRIPTION:
Mapping XS 875a5235
END DESCRIPTION:
XS GIS Cut Line= 3
      1668256.37      6925603.00      1668585.78      6925911.57
      1668980.14      6926278.61
#Sta/Elev= 30
  4551.0 1854.54  4572.4 1854.26  4616.4 1853.85  4666.8 1852.85  4702.0 1850.67
  4709.3 1851.41  4787.0 1846.00  4794.3 1846.60  4801.1 1844.73  4808.5 1844.74
  4862.2 1841.09  4867.2 1840.59  4900.3 1837.98  4935.5 1833.26  4949.6 1832.58
  4963.8 1833.20  4975.1 1832.20  4975.6 1831.70  4980.4 1831.70  4980.8 1832.20
  4985.3 1832.23  4998.4 1835.50  5013.6 1836.56  5035.4 1836.39  5042.4 1836.41
  5055.9 1835.88  5148.0 1836.37  5183.2 1835.54  5296.5 1838.31  5541.1 1840.98
#Mann=9,-1,0
  4551.0   0.035       0  4572.4    0.07       0  4616.4   0.035       0
  4862.2    0.07       0  4867.2   0.035       0  4975.1   0.035       0
  4980.8   0.035       0  5035.4    0.07       0  5042.4   0.035       0
Bank Sta=4975.1,4980.8
Exp/Cntr=0.3,0.1

Type RM Length L Ch R = 1,30984,193,193,193
BEGIN DESCRIPTION:
Mapping XS fb5d7e54
END DESCRIPTION:
XS GIS Cut Line= 3
      1668215.23      6925787.17      1668364.52      6926028.47
      1668704.75      6926253.56
#Sta/Elev= 30
  4717.2 1844.08  4783.1 1841.81  4788.9 1842.02  4804.3 1841.53  4835.1 1840.02
  4841.0 1840.87  4856.4 1839.30  4862.2 1839.46  4929.6 1837.13  4950.9 1835.73
  4972.2 1831.92  4987.6 1830.79  4994.9 1830.68  4995.3 1830.18  5000.1 1830.18
  5000.6 1830.68  5008.3 1830.68  5014.3 1832.05  5029.4 1834.44  5058.3 1834.76
  5080.6 1835.10  5101.6 1834.57  5152.8 1834.95  5209.9 1834.74  5276.2 1835.63
  5289.3 1835.37  5297.2 1835.80  5361.2 1836.45  5369.4 1836.92  5408.9 1837.17
#Mann=4,-1,0
  4717.2    0.07       0  4994.9    0.07       0  5000.6    0.07       0
  5058.3   0.035       0
Bank Sta=4994.9,5000.6
Exp/Cntr=0.3,0.1

Type RM Length L Ch R = 1,30791,148,148,148
BEGIN DESCRIPTION:
Mapping XS 7c659441
END DESCRIPTION:
XS GIS Cut Line= 3
      1667976.77      6925992.98      1668210.30      6926132.75
      1668361.55      6926244.47
#Sta/Elev= 30
  4727.9 1841.54  4760.8 1840.47  4772.6 1839.81  4825.1 1838.14  4830.9 1837.66
  4846.5 1837.32  4854.0 1837.92  4867.9 1836.42  4899.0 1835.85  4912.3 1835.47
  4919.7 1834.99  4920.4 1834.95  4926.2 1833.39  4941.8 1831.45  4947.6 1831.16
  4957.3 1831.26  4963.2 1830.37  4970.6 1829.85  4981.7 1829.82  4982.2 1829.32
  4987.0 1829.32  4987.4 1829.82  4993.9 1830.80  4999.9 1832.15  5006.3 1832.94
  5029.3 1833.93  5043.2 1834.26  5061.1 1834.39  5129.6 1834.85  5188.1 1834.75
#Mann=5,-1,0
  4727.9   0.035       0  4919.7    0.07       0  4981.7    0.07       0
  4987.4    0.07       0  5061.1   0.035       0
Bank Sta=4981.7,4987.4
Exp/Cntr=0.3,0.1

Type RM Length L Ch R = 1,30643,212,212,212
BEGIN DESCRIPTION:
Mapping XS f38f115c
END DESCRIPTION:
XS GIS Cut Line= 3
      1667954.61      6926108.42      1668106.54      6926237.78
      1668220.98      6926358.24
#Sta/Elev= 30
  4801.4 1839.31  4815.1 1838.91  4829.3 1838.14  4837.0 1838.00  4843.6 1838.26
  4857.9 1837.32  4872.2 1837.17  4886.4 1836.43  4893.9 1836.75  4907.3 1835.68
  4929.3 1834.66  4935.8 1834.57  4950.1 1833.52  4964.4 1829.49  4969.2 1829.36
  4969.7 1828.86  4974.6 1828.86  4975.0 1829.36  4985.8 1830.38  4993.0 1829.93
  5003.5 1829.87  5007.1 1830.55  5014.3 1830.75  5028.5 1831.68  5033.8 1832.22
  5056.4 1832.85  5084.7 1833.32  5092.0 1833.20  5127.2 1833.73  5167.1 1833.78
#Mann=4,-1,0
  4801.4   0.035       0  4969.2    0.07       0  4975.0   0.035       0
  5033.8   0.035       0
Bank Sta=4969.2,4975
Exp/Cntr=0.3,0.1

Type RM Length L Ch R = 1,30431,226,226,226
BEGIN DESCRIPTION:
Mapping XS df1c2528
END DESCRIPTION:
XS GIS Cut Line= 3
      1667759.82      6926123.05      1667958.64      6926389.56
      1668501.61      6926427.60
#Sta/Elev= 30
  4667.5 1841.00  4773.9 1838.61  4817.7 1836.91  4824.0 1837.37  4910.7 1834.20
  4932.4 1833.91  4967.8 1832.32  4982.4 1831.37  4988.7 1830.47  5000.0 1830.19
  5026.4 1828.49  5042.4 1828.25  5042.9 1827.75  5047.8 1827.75  5048.2 1828.25
  5056.5 1829.78  5066.5 1830.40  5176.8 1833.01  5186.8 1832.81  5236.9 1833.86
  5277.0 1833.73  5287.1 1833.26  5307.1 1833.57  5357.2 1833.15  5457.5 1833.56
  5475.5 1833.99  5487.6 1833.65  5527.7 1834.83  5537.7 1834.71  5544.3 1835.27
#Mann=3,-1,0
  4667.5   0.035       0  5042.4   0.035       0  5048.2   0.035       0
Bank Sta=5042.4,5048.2
Exp/Cntr=0.3,0.1

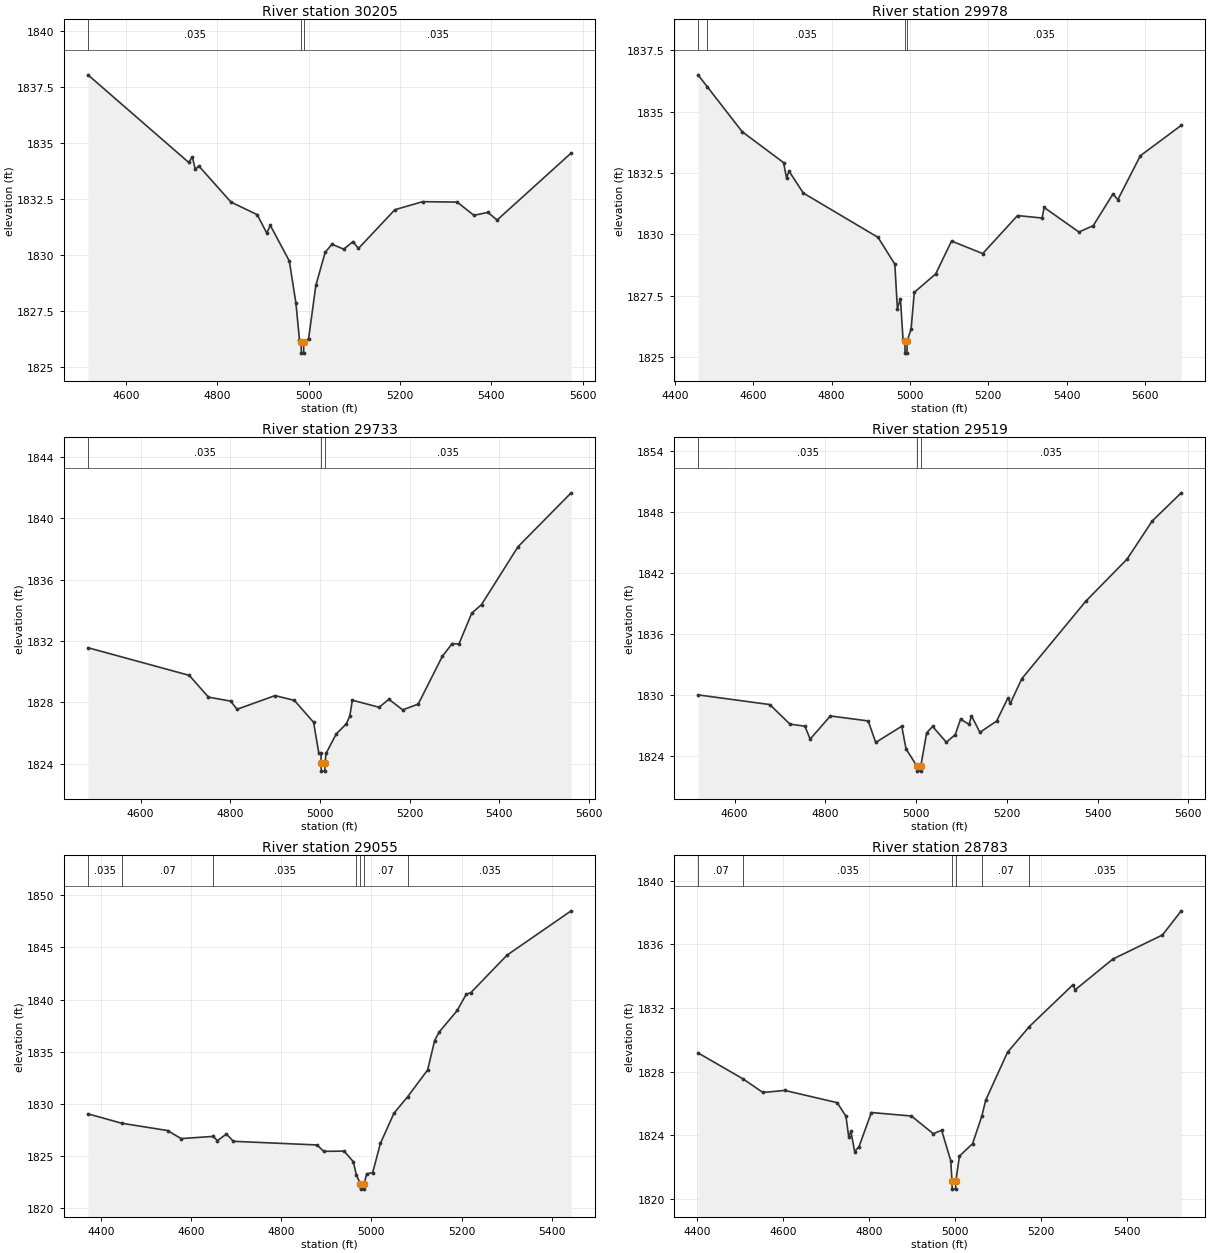
Type RM Length L Ch R = 1,30205,227,227,227
BEGIN DESCRIPTION:
Mapping XS 8d05210c
END DESCRIPTION:
XS GIS Cut Line= 3
      1667526.70      6926275.35      1667899.35      6926582.31
      1668464.26      6926477.19
#Sta/Elev= 30
  4517.2 1838.06  4737.7 1834.15  4745.6 1834.40  4752.1 1833.84  4759.9 1833.99
  4830.2 1832.38  4887.6 1831.82  4908.4 1831.00  4916.3 1831.34  4957.9 1829.75
  4972.3 1827.87  4980.1 1826.23  4983.7 1826.14  4984.2 1825.64  4989.1 1825.64
  4989.5 1826.14  5000.0 1826.28  5015.9 1828.66  5036.3 1830.14  5051.2 1830.50
  5076.9 1830.28  5097.3 1830.62  5109.0 1830.31  5188.8 1832.04  5249.9 1832.40
  5325.2 1832.38  5361.8 1831.79  5392.3 1831.92  5412.6 1831.58  5574.6 1834.57
#Mann=3,-1,0
  4517.2   0.035       0  4983.7   0.035       0  4989.5   0.035       0
Bank Sta=4983.7,4989.5
Exp/Cntr=0.3,0.1

Type RM Length L Ch R = 1,29978,245,245,245
BEGIN DESCRIPTION:
Mapping XS 36c14c15
END DESCRIPTION:
XS GIS Cut Line= 3
      1667452.54      6926352.22      1667804.60      6926763.00
      1668460.13      6926539.77
#Sta/Elev= 30
  4459.0 1836.50  4482.7 1836.01  4571.7 1834.18  4677.3 1832.92  4684.8 1832.30
  4691.3 1832.57  4727.6 1831.68  4918.5 1829.87  4961.3 1828.78  4967.9 1826.97
  4975.6 1827.37  4982.2 1825.74  4987.0 1825.65  4987.4 1825.15  4992.3 1825.15
  4992.8 1825.65  5002.9 1826.13  5011.0 1827.63  5065.6 1828.38  5106.1 1829.72
  5185.7 1829.21  5274.5 1830.76  5337.2 1830.66  5342.5 1831.09  5431.3 1830.09
  5467.9 1830.35  5518.1 1831.64  5530.6 1831.41  5588.1 1833.20  5692.5 1834.44
#Mann=4,-1,0
  4459.0    0.07       0  4482.7   0.035       0  4987.0   0.035       0
  4992.8   0.035       0
Bank Sta=4987,4992.8
Exp/Cntr=0.3,0.1

Type RM Length L Ch R = 1,29733,214,214,214
BEGIN DESCRIPTION:
Mapping XS 57189510
END DESCRIPTION:
XS GIS Cut Line= 3
      1667487.75      6926576.94      1667816.58      6926975.17
      1668086.67      6927467.51
#Sta/Elev= 30
  4482.6 1831.56  4708.5 1829.76  4751.5 1828.34  4801.0 1828.08  4815.3 1827.55
  4900.0 1828.44  4943.0 1828.13  4986.0 1826.70  4997.6 1824.70  5002.6 1824.70
  5002.7 1824.02  5003.2 1823.52  5010.9 1823.52  5011.4 1824.02  5013.7 1824.67
  5036.5 1825.94  5059.3 1826.61  5066.8 1827.12  5072.5 1828.14  5132.2 1827.68
  5154.0 1828.20  5184.8 1827.51  5219.4 1827.89  5273.4 1831.01  5295.2 1831.83
  5310.2 1831.80  5338.8 1833.81  5360.6 1834.37  5442.1 1838.14  5560.6 1841.65
#Mann=3,-1,0
  4482.6   0.035       0  5002.7   0.035       0  5011.4   0.035       0
Bank Sta=5002.7,5011.4
Exp/Cntr=0.3,0.1

Type RM Length L Ch R = 1,29519,464,464,464
BEGIN DESCRIPTION:
Mapping XS 2c4b203b
END DESCRIPTION:
XS GIS Cut Line= 3
      1667430.42      6926668.02      1667648.33      6927096.16
      1667852.01      6927643.81
#Sta/Elev= 30
  4519.6 1830.02  4677.6 1829.07  4722.1 1827.15  4755.2 1826.94  4766.6 1825.68
  4811.3 1827.95  4894.5 1827.46  4911.1 1825.35  4968.4 1826.94  4977.8 1824.73
  5001.7 1823.03  5002.2 1822.53  5009.9 1822.53  5010.4 1823.03  5023.3 1826.29
  5036.4 1826.92  5066.7 1825.37  5086.4 1826.12  5098.0 1827.63  5116.8 1827.13
  5122.1 1827.96  5140.7 1826.34  5177.5 1827.45  5202.5 1829.73  5207.8 1829.20
  5232.8 1831.60  5373.9 1839.22  5464.9 1843.36  5520.3 1847.10  5584.3 1849.87
#Mann=3,-1,0
  4519.6   0.035       0  5001.7   0.035       0  5010.4   0.035       0
Bank Sta=5001.7,5010.4
Exp/Cntr=0.3,0.1

Type RM Length L Ch R = 1,29055,272,272,272
BEGIN DESCRIPTION:
Mapping XS 0ccf6dac
END DESCRIPTION:
XS GIS Cut Line= 3
      1667297.62      6926712.29      1667360.70      6927338.74
      1667393.98      6927780.07
#Sta/Elev= 30
  4371.0 1829.06  4445.8 1828.16  4547.6 1827.46  4577.7 1826.69  4648.9 1826.90
  4658.2 1826.49  4678.3 1827.13  4693.7 1826.43  4879.3 1826.08  4894.1 1825.47
  4939.6 1825.49  4959.7 1824.48  4966.6 1823.22  4975.4 1822.35  4975.9 1821.85
  4983.6 1821.85  4984.1 1822.35  4989.2 1823.31  5002.8 1823.43  5019.9 1826.23
  5050.0 1829.12  5080.6 1830.71  5124.7 1833.26  5140.3 1836.08  5150.3 1836.89
  5190.4 1838.96  5210.5 1840.52  5220.5 1840.66  5300.7 1844.25  5443.2 1848.50
#Mann=7,-1,0
  4371.0   0.035       0  4445.8    0.07       0  4648.9   0.035       0
  4966.6    0.07       0  4975.4    0.07       0  4984.1    0.07       0
  5080.6   0.035       0
Bank Sta=4975.4,4984.1
Exp/Cntr=0.3,0.1

Type RM Length L Ch R = 1,28783,221,221,221
BEGIN DESCRIPTION:
Mapping XS c91cf9b7
END DESCRIPTION:
XS GIS Cut Line= 3
      1667214.29      6926699.31      1667105.14      6927287.67
      1667001.07      6927804.50
#Sta/Elev= 30
  4401.6 1829.17  4506.2 1827.54  4552.8 1826.68  4603.7 1826.81  4725.7 1826.04
  4746.1 1825.19  4752.6 1823.88  4757.7 1824.23  4766.4 1822.96  4776.6 1823.28
  4805.4 1825.42  4898.6 1825.20  4949.5 1824.09  4969.0 1824.30  4990.2 1822.40
  4993.2 1821.10  4993.7 1820.60  5001.5 1820.60  5002.0 1821.10  5010.5 1822.68
  5041.1 1823.46  5062.8 1825.21  5071.7 1826.20  5122.5 1829.21  5173.4 1830.83
  5275.0 1833.46  5280.1 1833.14  5367.6 1835.07  5483.4 1836.59  5527.2 1838.11
#Mann=6,-1,0
  4401.6    0.07       0  4506.2   0.035       0  4993.2   0.035       0
  5002.0   0.035       0  5062.8    0.07       0  5173.4   0.035       0
Bank Sta=4993.2,5002
Exp/Cntr=0.3,0.1

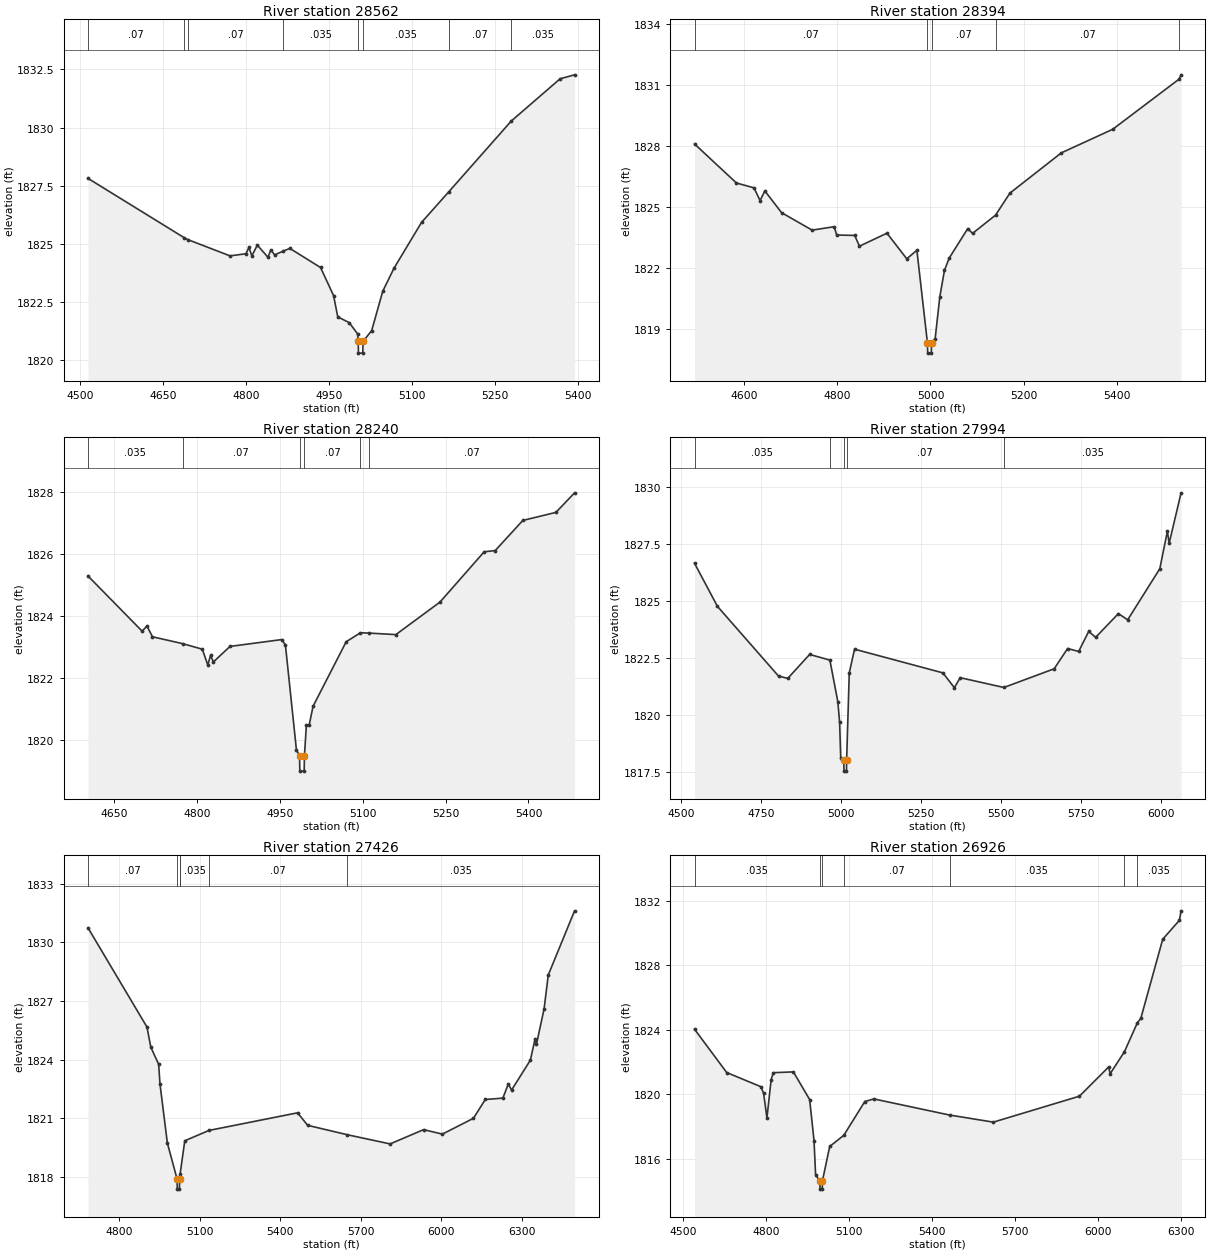
Type RM Length L Ch R = 1,28562,168,168,168
BEGIN DESCRIPTION:
Mapping XS d9aaeb87
END DESCRIPTION:
XS GIS Cut Line= 3
      1667047.64      6926733.12      1666917.85      6927202.46
      1666899.24      6927594.07
#Sta/Elev= 30
  4514.5 1827.82  4688.3 1825.27  4694.7 1825.19  4771.0 1824.49  4799.7 1824.58
  4805.3 1824.85  4810.5 1824.49  4820.4 1824.95  4839.7 1824.43  4844.8 1824.75
  4851.6 1824.53  4866.7 1824.69  4879.2 1824.81  4934.6 1823.99  4958.2 1822.78
  4965.7 1821.87  4986.4 1821.62  5001.5 1821.14  5002.6 1820.81  5003.1 1820.31
  5010.9 1820.31  5011.4 1820.81  5027.0 1821.28  5047.0 1822.97  5067.1 1823.95
  5117.1 1825.93  5166.2 1827.24  5279.0 1830.28  5367.4 1832.10  5393.5 1832.27
#Mann=8,-1,0
  4514.5    0.07       0  4688.3   0.035       0  4694.7    0.07       0
  4866.7   0.035       0  5002.6   0.035       0  5011.4   0.035       0
  5166.2    0.07       0  5279.0   0.035       0
Bank Sta=5002.6,5011.4
Exp/Cntr=0.3,0.1

Type RM Length L Ch R = 1,28394,154,154,154
BEGIN DESCRIPTION:
Mapping XS bf823048
END DESCRIPTION:
XS GIS Cut Line= 3
      1666862.72      6926639.47      1666774.06      6927139.10
      1666735.23      6927674.46
#Sta/Elev= 30
  4493.6 1828.09  4583.5 1826.17  4621.3 1825.93  4634.3 1825.30  4644.5 1825.78
  4680.4 1824.71  4746.0 1823.85  4793.5 1824.02  4798.6 1823.61  4837.4 1823.59
  4847.5 1823.06  4906.6 1823.70  4949.1 1822.44  4970.8 1822.86  4993.5 1818.30
  4994.0 1817.80  5001.8 1817.80  5002.3 1818.30  5010.0 1818.51  5020.0 1820.57
  5030.0 1821.87  5040.0 1822.47  5080.1 1823.93  5090.2 1823.69  5139.7 1824.59
  5170.4 1825.67  5280.7 1827.65  5391.0 1828.81  5533.6 1831.28  5537.8 1831.49
#Mann=5,-1,0
  4493.6    0.07       0  4993.5   0.035       0  5002.3    0.07       0
  5139.7    0.07       0  5533.6   0.035       0
Bank Sta=4993.5,5002.3
Exp/Cntr=0.3,0.1

Type RM Length L Ch R = 1,28240,246,246,246
BEGIN DESCRIPTION:
Mapping XS 9036e954
END DESCRIPTION:
XS GIS Cut Line= 3
      1666667.42      6926691.53      1666636.14      6927088.75
      1666636.17      6927571.70
#Sta/Elev= 30
  4602.1 1825.29  4700.2 1823.51  4708.9 1823.68  4718.9 1823.33  4773.3 1823.11
  4809.2 1822.93  4819.1 1822.42  4824.1 1822.73  4829.3 1822.52  4859.4 1823.02
  4953.0 1823.24  4959.7 1823.07  4979.7 1819.68  4985.3 1819.50  4985.8 1819.00
  4993.7 1819.00  4994.2 1819.50  4997.7 1820.48  5002.7 1820.48  5009.8 1821.09
  5069.8 1823.17  5095.7 1823.46  5110.7 1823.45  5159.8 1823.40  5239.8 1824.45
  5319.8 1826.07  5339.8 1826.11  5389.8 1827.08  5449.8 1827.34  5483.5 1827.97
#Mann=6,-1,0
  4602.1   0.035       0  4773.3    0.07       0  4985.3    0.07       0
  4994.2    0.07       0  5095.7   0.035       0  5110.7    0.07       0
Bank Sta=4985.3,4994.2
Exp/Cntr=0.3,0.1

Type RM Length L Ch R = 1,27994,568,568,568
BEGIN DESCRIPTION:
Mapping XS 9d6b0811
END DESCRIPTION:
XS GIS Cut Line= 3
      1666625.12      6926631.75      1666406.69      6927033.86
      1665994.13      6928014.18
#Sta/Elev= 30
  4542.4 1826.66  4614.0 1824.77  4805.0 1821.71  4834.0 1821.61  4902.3 1822.66
  4965.6 1822.41  4990.4 1820.59  4996.0 1819.69  4999.5 1818.11  5009.1 1818.04
  5009.6 1817.54  5017.5 1817.54  5018.0 1818.04  5026.2 1821.85  5042.7 1822.89
  5319.1 1821.85  5354.7 1821.20  5373.1 1821.64  5509.5 1821.21  5666.8 1822.03
  5708.8 1822.92  5743.4 1822.79  5774.8 1823.67  5796.5 1823.41  5867.5 1824.45
  5896.7 1824.18  5997.1 1826.42  6020.8 1828.07  6026.2 1827.53  6063.6 1829.75
#Mann=5,-1,0
  4542.4   0.035       0  4965.6    0.07       0  5009.1    0.07       0
  5018.0    0.07       0  5509.5   0.035       0
Bank Sta=5009.1,5018
Exp/Cntr=0.3,0.1

Type RM Length L Ch R = 1,27426,500,500,500
BEGIN DESCRIPTION:
Mapping XS 0131b86c
END DESCRIPTION:
XS GIS Cut Line= 3
      1666268.32      6926329.73      1666198.65      6926640.23
      1665879.05      6928098.71
#Sta/Elev= 30
  4684.6 1830.74  4904.2 1825.67  4918.5 1824.64  4947.6 1823.77  4952.7 1822.75
  4980.0 1819.75  5016.5 1817.89  5017.0 1817.39  5025.0 1817.39  5025.5 1817.89
  5027.3 1818.14  5044.9 1819.86  5135.2 1820.39  5465.0 1821.29  5502.2 1820.65
  5649.8 1820.17  5809.3 1819.70  5934.0 1820.43  6003.8 1820.20  6119.6 1821.01
  6163.5 1821.97  6229.0 1822.04  6249.5 1822.77  6261.4 1822.45  6331.4 1823.98
  6349.0 1825.07  6354.1 1824.79  6382.6 1826.61  6398.0 1828.33  6495.9 1831.61
#Mann=6,-1,0
  4684.6    0.07       0  5016.5    0.07       0  5025.5    0.07       0
  5027.3   0.035       0  5135.2    0.07       0  5649.8   0.035       0
Bank Sta=5016.5,5025.5
Exp/Cntr=0.3,0.1

Type RM Length L Ch R = 1,26926,171,171,171
BEGIN DESCRIPTION:
Mapping XS f155c1e1
END DESCRIPTION:
XS GIS Cut Line= 4
      1665582.19      6926481.53      1665813.01      6926880.20
      1665918.44      6926999.76      1665816.66      6928134.03
#Sta/Elev= 30
  4540.0 1824.03  4656.3 1821.34  4779.7 1820.46  4789.7 1820.06  4801.7 1818.51
  4817.0 1820.90  4824.8 1821.33  4897.4 1821.38  4956.2 1819.66  4972.0 1817.11
  4977.7 1814.99  4993.2 1814.60  4993.7 1814.10  5001.7 1814.10  5002.2 1814.60
  5028.7 1816.75  5079.5 1817.44  5155.6 1819.54  5188.4 1819.70  5462.0 1818.70
  5620.2 1818.26  5931.4 1819.87  6037.3 1821.69  6042.3 1821.26  6094.1 1822.63
  6140.6 1824.42  6153.4 1824.71  6232.6 1829.62  6292.8 1830.79  6298.9 1831.38
#Mann=7,-1,0
  4540.0   0.035       0  4993.2   0.035       0  5002.2   0.035       0
  5079.5    0.07       0  5462.0   0.035       0  6094.1    0.07       0
  6140.6   0.035       0
Bank Sta=4993.2,5002.2
Exp/Cntr=0.3,0.1