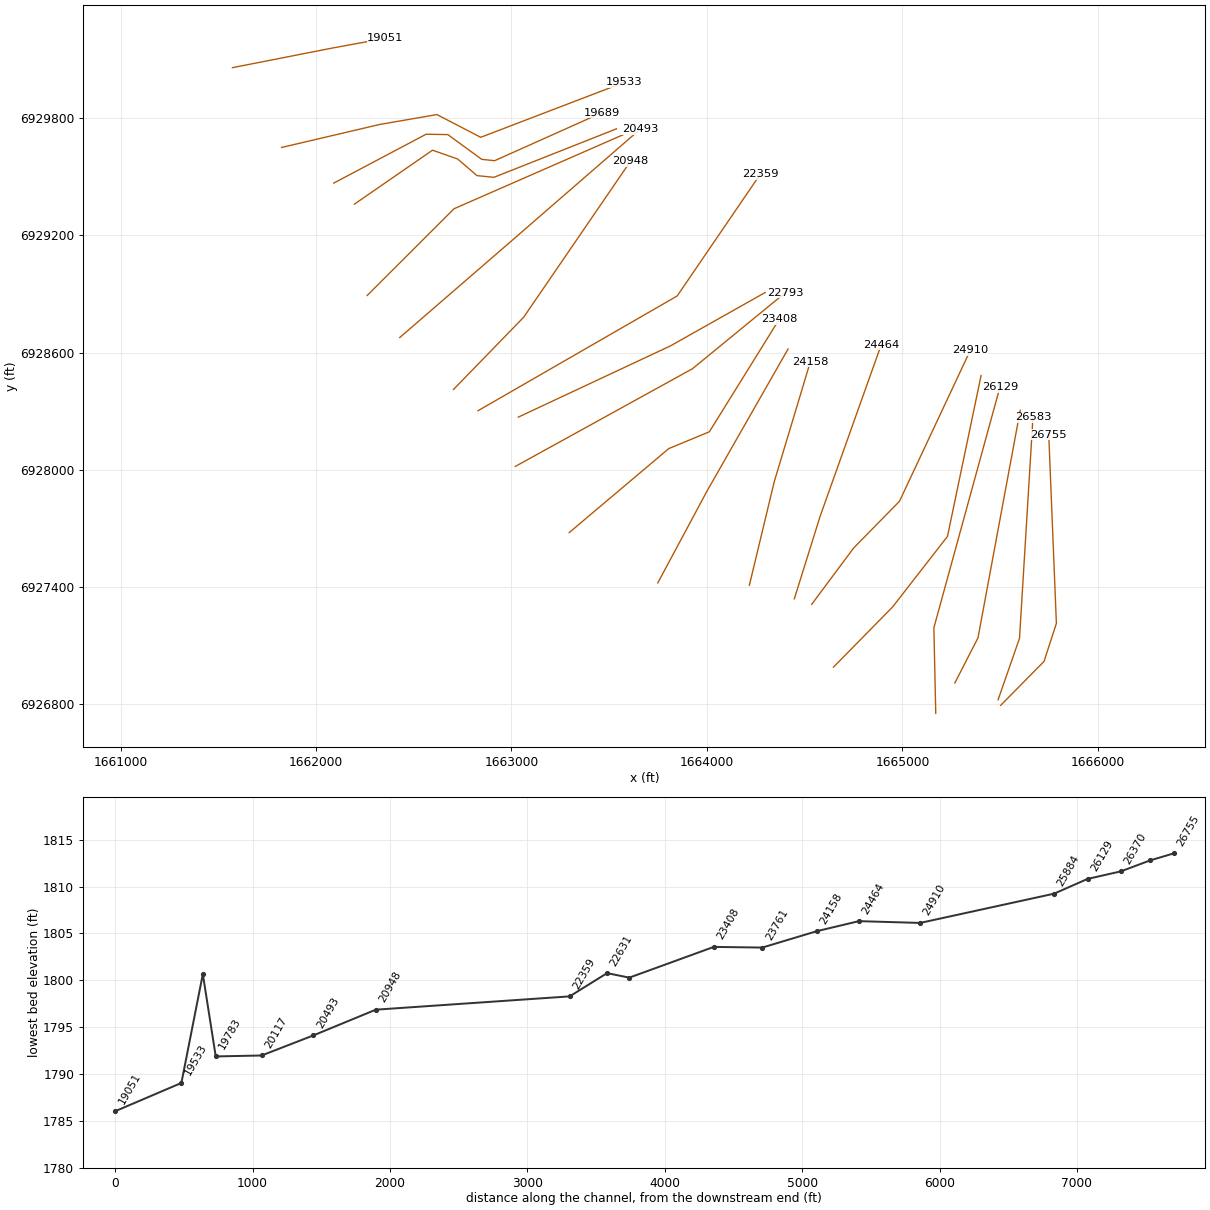
HEC-RAS study Chimney Creek 1097.prj: Chimney Creek 1097 Base Level Engineering

--- Chimney Creek 1097.g01 (geometry) --- (continued)

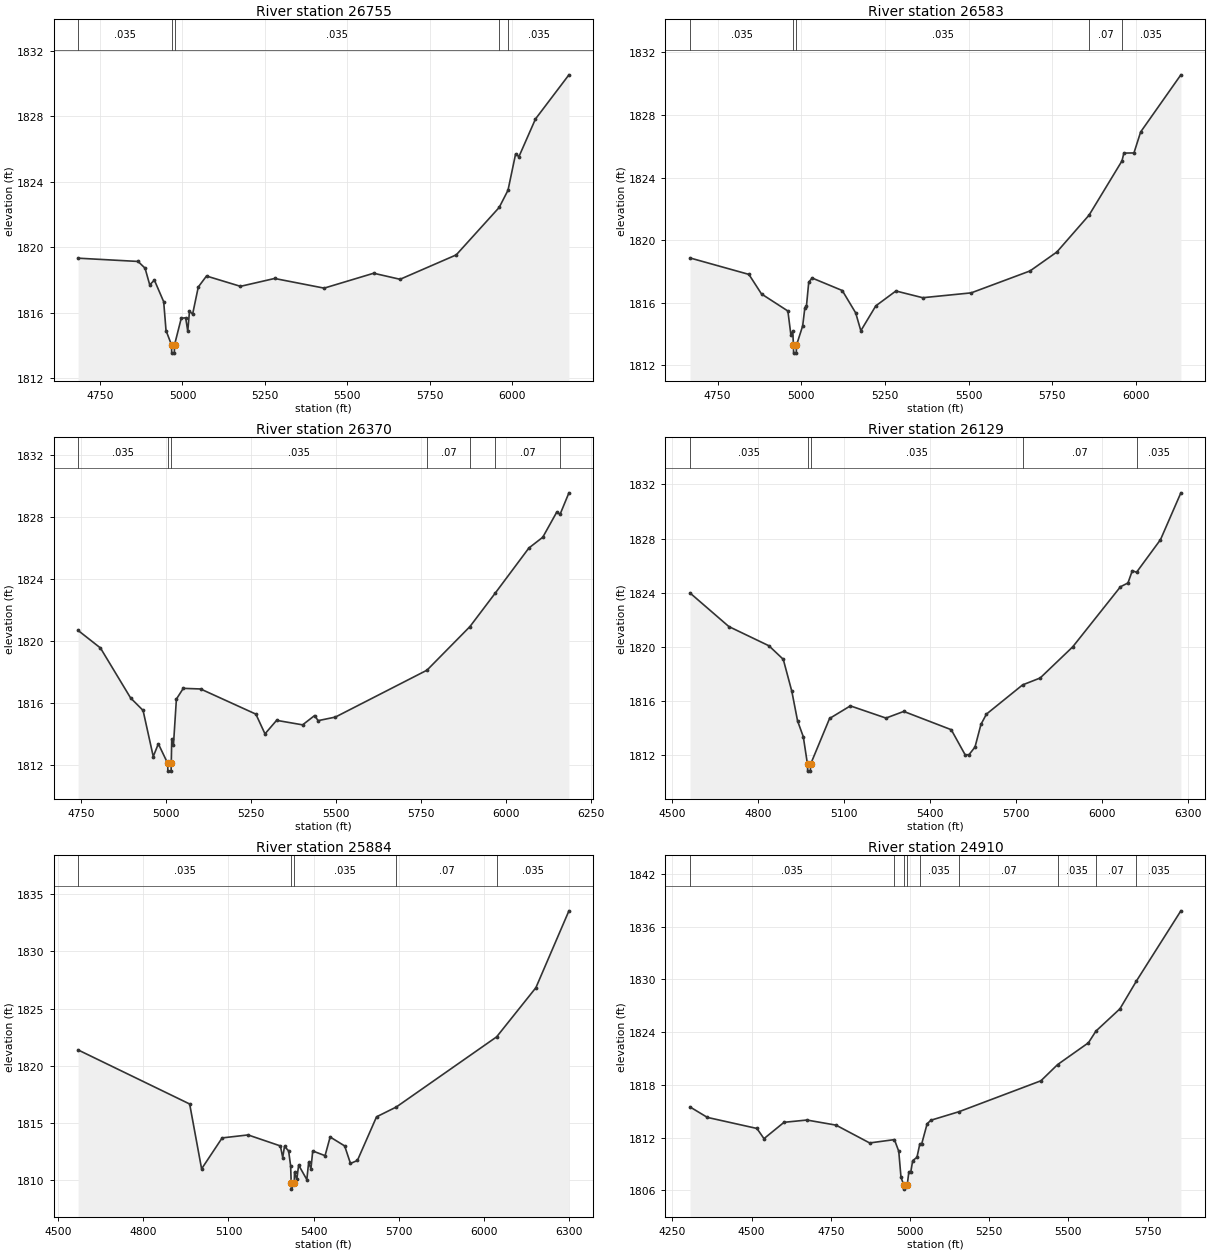
Type RM Length L Ch R = 1,26755,172,172,172
BEGIN DESCRIPTION:
Mapping XS f8477f1b
END DESCRIPTION:
XS GIS Cut Line= 4
      1665502.71      6926793.25      1665724.65      6927018.40
      1665787.91      6927213.27      1665748.85      6928179.46
#Sta/Elev= 30
  4683.5 1819.34  4865.3 1819.14  4886.5 1818.73  4900.7 1817.71  4914.8 1818.00
  4943.0 1816.68  4950.1 1814.92  4966.8 1814.04  4967.3 1813.54  4975.3 1813.54
  4975.8 1814.04  4996.3 1815.67  5009.7 1815.70  5016.0 1814.88  5021.2 1816.09
  5030.8 1815.93  5047.9 1817.58  5072.8 1818.25  5175.8 1817.62  5279.3 1818.10
  5429.4 1817.51  5579.6 1818.42  5659.6 1818.05  5829.8 1819.54  5960.1 1822.44
  5986.8 1823.49  6009.9 1825.71  6019.9 1825.54  6070.0 1827.84  6171.5 1830.54
#Mann=5,-1,0
  4683.5   0.035       0  4966.8   0.035       0  4975.8   0.035       0
  5960.1    0.07       0  5986.8   0.035       0
Bank Sta=4966.8,4975.8
Exp/Cntr=0.3,0.1

Type RM Length L Ch R = 1,26583,213,213,213
BEGIN DESCRIPTION:
Mapping XS b5b2377d
END DESCRIPTION:
XS GIS Cut Line= 3
      1665489.67      6926821.85      1665599.22      6927136.89
      1665668.12      6928267.95
#Sta/Elev= 30
  4667.4 1818.87  4843.3 1817.82  4881.0 1816.57  4959.8 1815.48  4969.0 1813.92
  4974.3 1814.21  4976.4 1813.29  4976.9 1812.79  4984.9 1812.79  4985.4 1813.29
  5004.0 1814.53  5010.4 1815.67  5015.4 1815.82  5022.1 1817.32  5032.1 1817.59
  5122.3 1816.79  5162.4 1815.36  5177.8 1814.22  5222.5 1815.81  5282.6 1816.76
  5362.7 1816.33  5507.6 1816.64  5683.3 1818.04  5763.5 1819.25  5859.9 1821.61
  5958.1 1825.07  5963.8 1825.57  5993.9 1825.58  6013.9 1826.92  6134.1 1830.57
#Mann=5,-1,0
  4667.4   0.035       0  4976.4   0.035       0  4985.4   0.035       0
  5859.9    0.07       0  5958.1   0.035       0
Bank Sta=4976.4,4985.4
Exp/Cntr=0.3,0.1

Type RM Length L Ch R = 1,26370,241,241,241
BEGIN DESCRIPTION:
Mapping XS b8cc93a6
END DESCRIPTION:
XS GIS Cut Line= 3
      1665268.31      6926907.79      1665386.89      6927139.27
      1665602.88      6928303.73
#Sta/Elev= 30
  4741.4 1820.68  4807.2 1819.55  4896.0 1816.33  4932.6 1815.53  4962.6 1812.56
  4977.6 1813.38  5005.1 1812.12  5005.6 1811.62  5015.1 1811.62  5015.6 1812.12
  5017.0 1813.70  5022.1 1813.32  5030.7 1816.26  5051.0 1816.95  5101.9 1816.91
  5264.6 1815.29  5291.4 1814.02  5325.6 1814.89  5402.1 1814.60  5437.5 1815.20
  5447.7 1814.87  5498.5 1815.10  5768.1 1818.12  5894.6 1820.93  5968.2 1823.06
  6068.1 1825.99  6108.8 1826.68  6149.5 1828.28  6160.0 1828.17  6185.8 1829.54
#Mann=7,-1,0
  4741.4   0.035       0  5005.1   0.035       0  5015.6   0.035       0
  5768.1    0.07       0  5894.6   0.035       0  5968.2    0.07       0
  6160.0   0.035       0
Bank Sta=5005.1,5015.6
Exp/Cntr=0.3,0.1

Type RM Length L Ch R = 1,26129,245,245,245
BEGIN DESCRIPTION:
Mapping XS 615462c5
END DESCRIPTION:
XS GIS Cut Line= 3
      1665170.72      6926752.38      1665161.11      6927190.68
      1665498.84      6928421.58
#Sta/Elev= 30
  4561.6 1823.98  4697.3 1821.50  4837.3 1820.08  4887.3 1819.08  4917.3 1816.71
  4937.3 1814.53  4957.3 1813.36  4972.0 1811.32  4972.5 1810.82  4982.1 1810.82
  4982.6 1811.32  5049.1 1814.71  5121.7 1815.64  5246.1 1814.74  5308.3 1815.23
  5474.2 1813.88  5522.9 1812.02  5536.4 1812.04  5557.2 1812.60  5577.9 1814.27
  5597.0 1815.03  5723.4 1817.19  5784.8 1817.70  5898.5 1820.00  6065.3 1824.44
  6091.5 1824.72  6106.8 1825.63  6121.5 1825.51  6205.2 1827.92  6276.4 1831.38
#Mann=5,-1,0
  4561.6   0.035       0  4972.0   0.035       0  4982.6   0.035       0
  5723.4    0.07       0  6121.5   0.035       0
Bank Sta=4972,4982.6
Exp/Cntr=0.3,0.1

Type RM Length L Ch R = 1,25884,974,974,974
BEGIN DESCRIPTION:
Mapping XS 262eb2ff
END DESCRIPTION:
XS GIS Cut Line= 4
      1664647.40      6926989.15      1664948.93      6927296.13
      1665230.71      6927658.40      1665402.59      6928482.00
#Sta/Elev= 30
  4569.7 1821.39  4963.1 1816.67  5005.2 1811.01  5077.6 1813.71  5169.0 1813.97
  5283.0 1813.01  5291.2 1812.00  5297.5 1812.97  5312.0 1812.58  5319.1 1811.27
  5321.2 1809.74  5321.7 1809.24  5331.8 1809.74  5332.8 1810.73  5340.9 1810.09
  5347.3 1811.34  5376.2 1810.07  5382.6 1811.57  5390.7 1811.02  5397.0 1812.57
  5440.5 1812.16  5458.4 1813.79  5509.6 1813.01  5530.1 1811.48  5554.5 1811.74
  5622.0 1815.55  5691.8 1816.41  6045.4 1822.53  6183.8 1826.82  6300.3 1833.53
#Mann=5,-1,0
  4569.7   0.035       0  5321.2   0.035       0  5331.8   0.035       0
  5691.8    0.07       0  6045.4   0.035       0
Bank Sta=5321.2,5331.8
Exp/Cntr=0.3,0.1

Type RM Length L Ch R = 1,24910,446,446,446
BEGIN DESCRIPTION:
Mapping XS ae7efc1a
END DESCRIPTION:
XS GIS Cut Line= 4
      1664536.10      6927310.80      1664750.93      6927599.42
      1664985.03      6927838.07      1665347.88      6928612.14
#Sta/Elev= 30
  4305.9 1815.48  4360.6 1814.29  4517.0 1813.03  4539.3 1811.87  4602.5 1813.73
  4674.7 1813.99  4766.6 1813.41  4872.7 1811.38  4950.9 1811.76  4964.6 1810.43
  4971.7 1807.45  4980.4 1806.62  4980.9 1806.12  4991.4 1806.62  4996.5 1808.10
  5002.7 1808.10  5008.6 1809.37  5022.0 1809.74  5030.7 1811.21  5036.9 1811.26
  5054.2 1813.57  5066.2 1813.97  5154.7 1814.94  5413.2 1818.46  5466.0 1820.31
  5563.2 1822.79  5586.8 1824.12  5662.6 1826.66  5714.7 1829.83  5854.9 1837.82
#Mann=9,-1,0
  4305.9   0.035       0  4950.9    0.07       0  4980.4    0.07       0
  4991.4    0.07       0  5030.7   0.035       0  5154.7    0.07       0
  5466.0   0.035       0  5586.8    0.07       0  5714.7   0.035       0
Bank Sta=4980.4,4991.4
Exp/Cntr=0.3,0.1

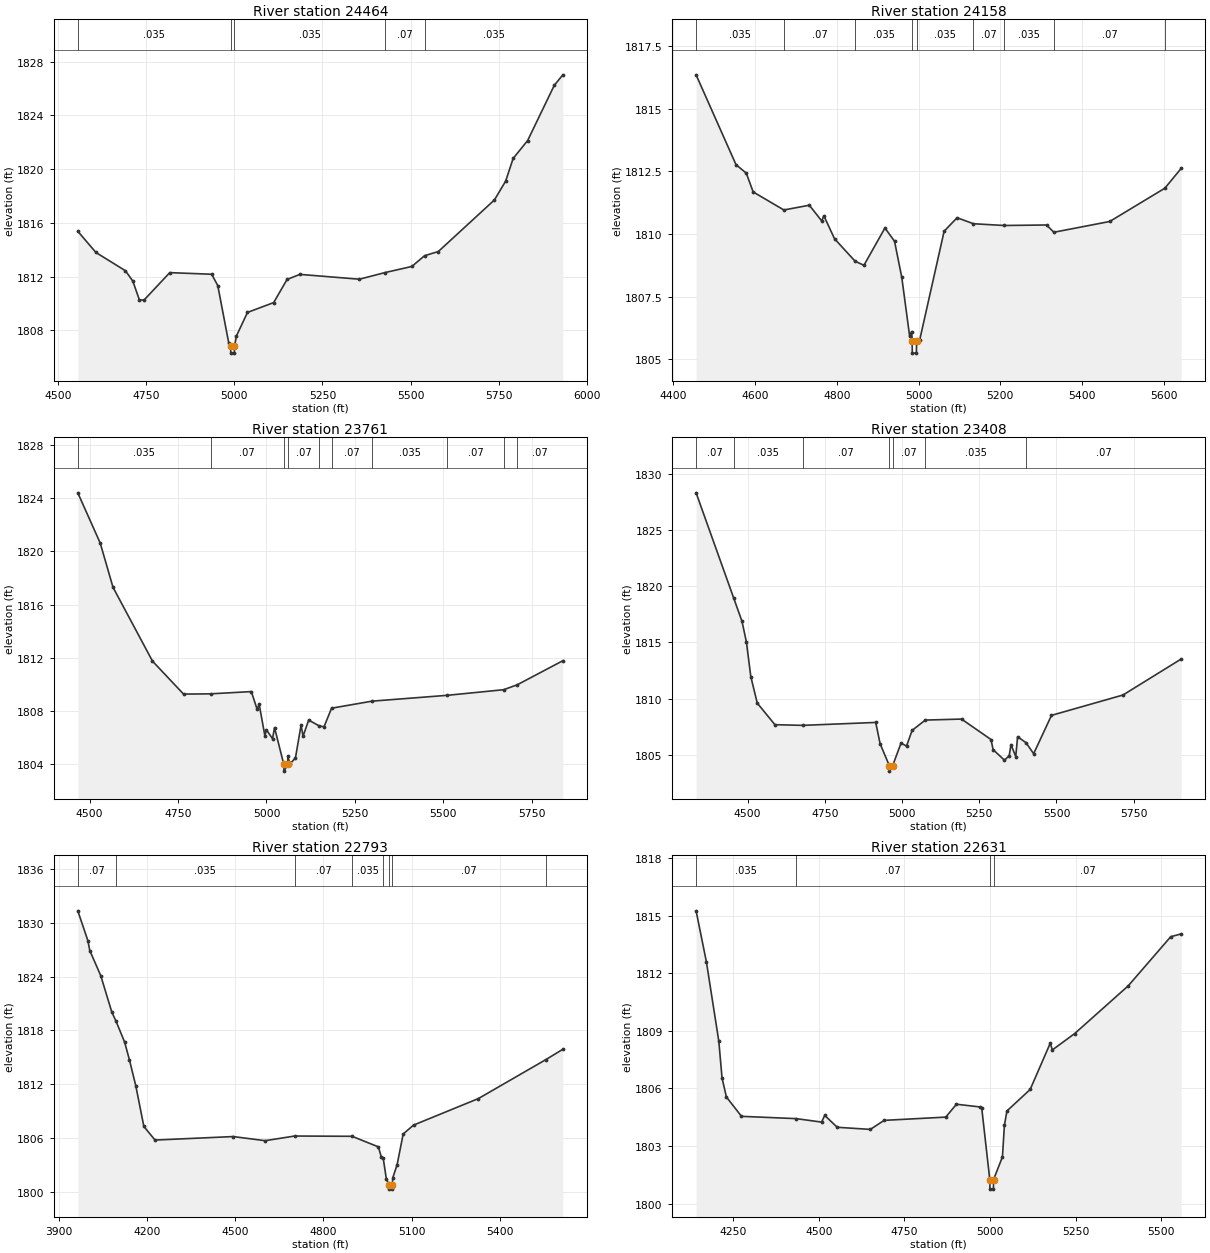
Type RM Length L Ch R = 1,24464,306,306,306
BEGIN DESCRIPTION:
Mapping XS 004063eb
END DESCRIPTION:
XS GIS Cut Line= 3
      1664447.10      6927338.97      1664579.61      6927762.93
      1664892.19      6928640.87
#Sta/Elev= 30
  4556.0 1815.38  4607.4 1813.80  4691.2 1812.44  4712.1 1811.67  4730.6 1810.28
  4743.6 1810.25  4816.9 1812.30  4935.9 1812.18  4953.1 1811.34  4984.5 1807.03
  4989.5 1806.81  4990.0 1806.31  5000.0 1806.31  5000.5 1806.81  5006.1 1807.59
  5037.4 1809.34  5111.7 1810.07  5149.6 1811.79  5186.0 1812.17  5354.8 1811.81
  5427.0 1812.30  5503.7 1812.76  5539.8 1813.56  5578.8 1813.87  5738.0 1817.71
  5769.8 1819.11  5791.1 1820.80  5832.2 1822.13  5907.8 1826.24  5932.1 1827.02
#Mann=5,-1,0
  4556.0   0.035       0  4989.5   0.035       0  5000.5   0.035       0
  5427.0    0.07       0  5539.8   0.035       0
Bank Sta=4989.5,5000.5
Exp/Cntr=0.3,0.1

Type RM Length L Ch R = 1,24158,397,397,397
BEGIN DESCRIPTION:
Mapping XS 9b8ac339
END DESCRIPTION:
XS GIS Cut Line= 3
      1664217.08      6927408.46      1664344.44      6927938.71
      1664529.40      6928553.67
#Sta/Elev= 30
  4455.5 1816.36  4553.2 1812.77  4578.4 1812.43  4595.2 1811.68  4670.4 1810.96
  4732.7 1811.15  4763.1 1810.52  4768.2 1810.73  4794.4 1809.81  4844.9 1808.91
  4866.4 1808.75  4917.8 1810.24  4941.3 1809.71  4959.0 1808.27  4978.1 1805.94
  4983.2 1806.10  4984.3 1805.74  4984.8 1805.24  4994.8 1805.24  4995.3 1805.74
  5003.1 1805.78  5062.7 1810.11  5094.4 1810.65  5134.6 1810.41  5209.5 1810.34
  5313.4 1810.36  5331.4 1810.07  5468.1 1810.50  5603.1 1811.83  5643.0 1812.62
#Mann=9,-1,0
  4455.5   0.035       0  4670.4    0.07       0  4844.9   0.035       0
  4984.3   0.035       0  4995.3   0.035       0  5134.6    0.07       0
  5209.5   0.035       0  5331.4    0.07       0  5603.1   0.035       0
Bank Sta=4984.3,4995.3
Exp/Cntr=0.3,0.1

Type RM Length L Ch R = 1,23761,353,353,353
BEGIN DESCRIPTION:
Mapping XS e2909efc
END DESCRIPTION:
XS GIS Cut Line= 3
      1663748.52      6927420.26      1664000.56      6927890.85
      1664415.17      6928618.14
#Sta/Elev= 30
  4466.7 1824.41  4530.0 1820.64  4566.2 1817.31  4677.8 1811.76  4765.6 1809.28
  4841.9 1809.30  4957.3 1809.47  4973.6 1808.13  4979.2 1808.53  4995.5 1806.15
  4999.9 1806.59  5017.1 1805.93  5022.8 1806.76  5049.0 1803.99  5049.5 1803.49
  5060.1 1803.99  5060.3 1804.59  5066.3 1804.03  5081.9 1804.48  5097.7 1806.94
  5103.5 1806.12  5119.3 1807.33  5148.2 1806.90  5162.6 1806.82  5184.0 1808.22
  5298.4 1808.75  5511.6 1809.19  5670.2 1809.61  5708.8 1809.98  5837.7 1811.79
#Mann=10,-1,0
  4466.7   0.035       0  4841.9    0.07       0  5049.0    0.07       0
  5060.1    0.07       0  5148.2   0.035       0  5184.0    0.07       0
  5298.4   0.035       0  5511.6    0.07       0  5670.2   0.035       0
  5708.8    0.07       0
Bank Sta=5049,5060.1
Exp/Cntr=0.3,0.1

Type RM Length L Ch R = 1,23408,615,615,615
BEGIN DESCRIPTION:
Mapping XS 08bf6d80
END DESCRIPTION:
XS GIS Cut Line= 4
      1663295.41      6927678.07      1663804.79      6928108.07
      1664012.43      6928194.10      1664370.46      6928771.08
#Sta/Elev= 30
  4333.4 1828.31  4454.9 1818.97  4482.0 1816.88  4496.3 1815.04  4510.5 1811.97
  4531.4 1809.61  4588.6 1807.69  4678.9 1807.63  4914.9 1807.89  4929.2 1805.99
  4958.8 1804.06  4959.3 1803.56  4969.9 1804.06  4996.9 1806.05  5014.7 1805.79
  5032.7 1807.18  5075.3 1808.10  5192.7 1808.19  5288.2 1806.37  5295.0 1805.47
  5331.7 1804.53  5347.0 1804.93  5352.9 1805.91  5368.3 1804.86  5374.2 1806.62
  5401.4 1806.09  5426.2 1805.11  5484.0 1808.52  5715.5 1810.33  5903.8 1813.53
#Mann=7,-1,0
  4333.4    0.07       0  4454.9   0.035       0  4678.9    0.07       0
  4958.8    0.07       0  4969.9    0.07       0  5075.3   0.035       0
  5401.4    0.07       0
Bank Sta=4958.8,4969.9
Exp/Cntr=0.3,0.1

Type RM Length L Ch R = 1,22793,162,162,162
BEGIN DESCRIPTION:
Mapping XS f93c3704
END DESCRIPTION:
XS GIS Cut Line= 3
      1663019.32      6928016.58      1663925.99      6928516.99
      1664401.04      6928906.30
#Sta/Elev= 30
  3964.4 1831.36  3998.9 1828.01  4005.2 1826.92  4042.5 1824.12  4080.3 1820.03
  4093.5 1819.11  4123.8 1816.69  4139.9 1814.73  4161.6 1811.83  4189.1 1807.28
  4227.0 1805.76  4492.8 1806.15  4601.7 1805.69  4701.8 1806.21  4897.2 1806.18
  4986.7 1805.00  4996.6 1803.89  5003.0 1803.77  5013.8 1801.44  5022.6 1800.78
  5023.1 1800.28  5033.2 1800.28  5033.7 1800.78  5036.0 1801.57  5050.4 1803.00
  5071.2 1806.44  5106.4 1807.43  5326.7 1810.39  5556.7 1814.75  5614.2 1815.90
#Mann=8,-1,0
  3964.4    0.07       0  4093.5   0.035       0  4701.8    0.07       0
  4897.2   0.035       0  5003.0    0.07       0  5022.6   0.035       0
  5033.7    0.07       0  5556.7   0.035       0
Bank Sta=5022.6,5033.7
Exp/Cntr=0.3,0.1

Type RM Length L Ch R = 1,22631,272,272,272
BEGIN DESCRIPTION:
Mapping XS f0d3b8f5
END DESCRIPTION:
XS GIS Cut Line= 3
      1663034.98      6928269.20      1663812.37      6928633.39
      1664298.01      6928907.23
#Sta/Elev= 30
  4142.0 1815.25  4172.1 1812.59  4208.3 1808.46  4217.7 1806.55  4230.4 1805.56
  4274.5 1804.55  4434.5 1804.43  4508.3 1804.25  4517.5 1804.60  4553.9 1803.98
  4650.7 1803.87  4690.9 1804.34  4870.9 1804.51  4901.9 1805.18  4970.2 1805.04
  4975.9 1804.97  4999.3 1801.26  4999.8 1800.76  5009.9 1800.76  5010.4 1801.26
  5036.3 1802.44  5042.0 1804.08  5049.4 1804.83  5117.2 1805.95  5175.7 1808.35
  5182.2 1808.01  5247.2 1808.86  5403.2 1811.34  5527.4 1813.90  5558.0 1814.05
#Mann=4,-1,0
  4142.0   0.035       0  4434.5    0.07       0  4999.3    0.07       0
  5010.4    0.07       0
Bank Sta=4999.3,5010.4
Exp/Cntr=0.3,0.1

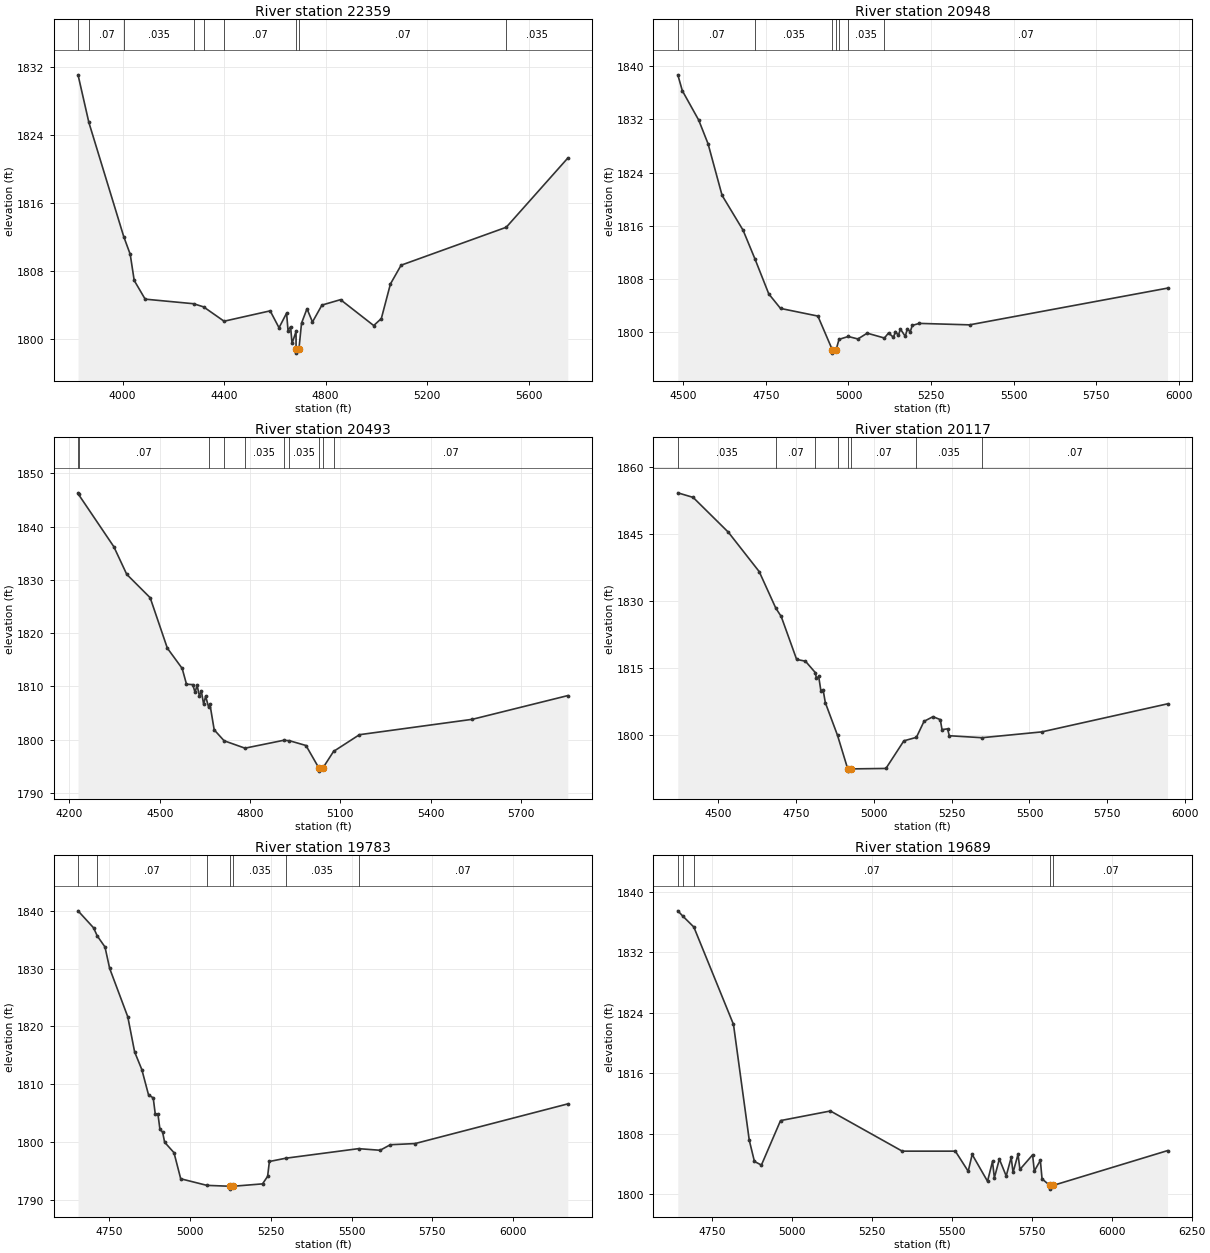
Type RM Length L Ch R = 1,22359,1411,1411,1411
BEGIN DESCRIPTION:
Mapping XS 62338d27
END DESCRIPTION:
XS GIS Cut Line= 3
      1662828.92      6928302.02      1663847.79      6928889.55
      1664272.54      6929512.13
#Sta/Elev= 30
  3824.2 1831.07  3866.9 1825.46  4004.4 1812.00  4029.8 1809.93  4045.6 1806.84
  4088.7 1804.64  4279.7 1804.10  4318.9 1803.73  4399.7 1802.04  4581.3 1803.26
  4616.2 1801.27  4646.0 1802.99  4651.7 1800.94  4661.8 1801.39  4667.5 1799.43
  4683.3 1800.83  4683.4 1798.78  4683.9 1798.28  4694.7 1798.78  4704.9 1801.81
  4726.4 1803.51  4748.0 1801.95  4785.3 1803.94  4858.6 1804.58  4989.3 1801.53
  5019.3 1802.35  5055.2 1806.43  5097.2 1808.64  5511.6 1813.11  5754.0 1821.26
#Mann=9,-1,0
  3824.2   0.035       0  3866.9    0.07       0  4004.4   0.035       0
  4279.7    0.07       0  4318.9   0.035       0  4399.7    0.07       0
  4683.4    0.07       0  4694.7    0.07       0  5511.6   0.035       0
Bank Sta=4683.4,4694.7
Exp/Cntr=0.3,0.1

Type RM Length L Ch R = 1,20948,455,455,455
BEGIN DESCRIPTION:
Mapping XS b262340a
END DESCRIPTION:
XS GIS Cut Line= 3
      1662703.06      6928410.52      1663062.75      6928781.18
      1663608.03      6929578.09
#Sta/Elev= 30
  4483.5 1838.69  4497.2 1836.30  4546.8 1831.88  4575.1 1828.32  4617.5 1820.57
  4681.1 1815.33  4717.2 1810.99  4758.8 1805.76  4794.3 1803.58  4907.4 1802.43
  4951.1 1797.36  4951.6 1796.86  4962.5 1797.36  4971.4 1798.93  4999.3 1799.36
  5028.5 1798.99  5056.7 1799.86  5108.8 1799.13  5121.2 1799.89  5136.1 1799.24
  5142.2 1800.10  5151.1 1799.53  5157.1 1800.48  5172.0 1799.38  5178.1 1800.53
  5186.9 1800.06  5193.0 1801.02  5214.2 1801.33  5366.4 1801.11  5965.6 1806.63
#Mann=7,-1,0
  4483.5    0.07       0  4717.2   0.035       0  4951.1   0.035       0
  4962.5   0.035       0  4971.4    0.07       0  4999.3   0.035       0
  5108.8    0.07       0
Bank Sta=4951.1,4962.5
Exp/Cntr=0.3,0.1

Type RM Length L Ch R = 1,20493,376,376,376
BEGIN DESCRIPTION:
Mapping XS b63c357c
END DESCRIPTION:
XS GIS Cut Line= 3
      1662428.31      6928676.58      1663011.76      6929181.51
      1663657.47      6929742.55
#Sta/Elev= 30
  4228.4 1846.36  4230.0 1846.07  4347.4 1836.24  4390.2 1831.06  4468.1 1826.66
  4525.1 1817.20  4574.4 1813.39  4588.7 1810.43  4609.6 1810.35  4617.2 1808.89
  4623.8 1810.24  4631.5 1808.26  4638.1 1809.12  4645.7 1806.67  4652.3 1808.18
  4662.5 1806.06  4666.6 1806.66  4680.8 1801.86  4713.7 1799.81  4783.1 1798.42
  4911.6 1799.90  4930.8 1799.82  4985.7 1798.92  5029.4 1794.61  5029.9 1794.11
  5040.8 1794.61  5077.3 1797.81  5163.3 1800.95  5538.4 1803.84  5855.4 1808.29
#Mann=10,-1,0
  4228.4   0.035       0  4230.0    0.07       0  4662.5   0.035       0
  4713.7    0.07       0  4783.1   0.035       0  4911.6    0.07       0
  4930.8   0.035       0  5029.4   0.035       0  5040.8   0.035       0
  5077.3    0.07       0
Bank Sta=5029.4,5040.8
Exp/Cntr=0.3,0.1

Type RM Length L Ch R = 1,20117,334,334,334
BEGIN DESCRIPTION:
Mapping XS 46181c28
END DESCRIPTION:
XS GIS Cut Line= 3
      1662261.67      6928891.88      1662706.03      6929336.05
      1663570.36      6929714.65
#Sta/Elev= 30
  4371.3 1854.17  4420.4 1853.15  4533.5 1845.37  4632.5 1836.57  4685.7 1828.42
  4703.2 1826.53  4752.7 1816.94  4781.0 1816.54  4812.5 1814.00  4816.4 1812.68
  4823.5 1813.12  4830.5 1809.96  4837.6 1810.19  4844.7 1807.29  4883.9 1799.97
  4916.7 1792.47  4917.2 1791.97  4928.2 1792.47  5039.3 1792.57  5096.9 1798.74
  5137.1 1799.52  5161.6 1803.10  5190.4 1804.14  5213.8 1803.48  5219.3 1801.25
  5237.2 1801.42  5242.7 1799.88  5347.6 1799.44  5539.6 1800.74  5943.2 1807.01
#Mann=8,-1,0
  4371.3   0.035       0  4685.7    0.07       0  4812.5   0.035       0
  4883.9    0.07       0  4916.7    0.07       0  4928.2    0.07       0
  5137.1   0.035       0  5347.6    0.07       0
Bank Sta=4916.7,4928.2
Exp/Cntr=0.3,0.1

Type RM Length L Ch R = 1,19783,94,94,94
BEGIN DESCRIPTION:
Mapping XS d66f70a9
END DESCRIPTION:
XS GIS Cut Line= 6
      1662196.72      6929359.85      1662596.01      6929635.88
      1662724.48      6929590.74      1662823.44      6929505.67
      1662910.24      6929496.99      1663536.96      6929745.24
#Sta/Elev= 30
  4653.3 1840.00  4701.4 1837.06  4712.8 1835.66  4736.7 1833.75  4751.2 1830.04
  4807.3 1821.67  4828.4 1815.61  4850.7 1812.55  4871.5 1808.17  4886.0 1807.65
  4892.3 1804.86  4900.5 1804.88  4906.8 1802.21  4915.0 1801.74  4921.3 1799.98
  4950.3 1798.17  4971.1 1793.66  5052.2 1792.52  5122.5 1792.37  5123.0 1791.87
  5134.0 1792.37  5224.3 1792.78  5240.0 1794.08  5245.5 1796.65  5296.7 1797.22
  5521.3 1798.87  5588.1 1798.59  5619.9 1799.55  5696.4 1799.75  6168.9 1806.61
#Mann=7,-1,0
  4653.3   0.035       0  4712.8    0.07       0  5052.2   0.035       0
  5122.5    0.07       0  5134.0   0.035       0  5296.7   0.035       0
  5521.3    0.07       0
Bank Sta=5122.5,5134
Exp/Cntr=0.3,0.1

Type RM Length L Ch R = 1,19689,156,156,156
BEGIN DESCRIPTION:
Mapping XS 4572dc2e
END DESCRIPTION:
XS GIS Cut Line= 6
      1662090.81      6929467.48      1662563.02      6929717.47
      1662674.13      6929715.74      1662847.74      6929589.00
      1662913.71      6929582.06      1663464.07      6929828.59
#Sta/Elev= 30
  4643.1 1837.45  4659.5 1836.72  4693.2 1835.31  4817.2 1822.43  4866.6 1807.11
  4882.7 1804.32  4904.5 1803.84  4964.3 1809.72  5120.3 1810.99  5344.8 1805.68
  5510.9 1805.68  5551.1 1803.02  5563.5 1805.24  5611.5 1801.70  5627.1 1804.32
  5632.9 1802.15  5648.5 1804.63  5669.9 1802.40  5685.5 1804.85  5691.3 1802.87
  5706.9 1805.26  5712.8 1803.26  5752.4 1805.19  5757.8 1803.05  5776.7 1804.46
  5782.0 1802.01  5805.9 1801.16  5806.4 1800.66  5817.4 1801.16  6174.4 1805.75
#Mann=5,-1,0
  4643.1    0.07       0  4659.5   0.035       0  4693.2    0.07       0
  5805.9    0.07       0  5817.4    0.07       0
Bank Sta=5805.9,5817.4
Exp/Cntr=0.3,0.1

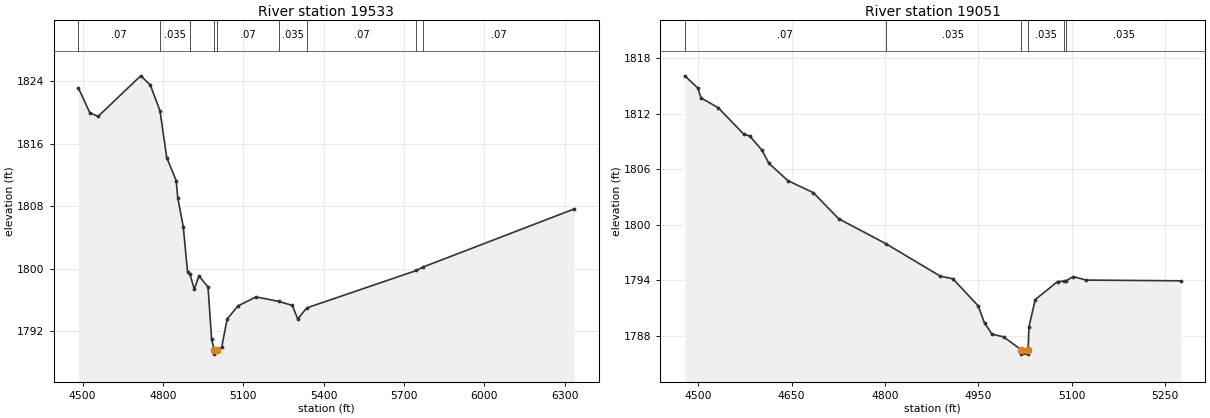
Type RM Length L Ch R = 1,19533,482,482,482
BEGIN DESCRIPTION:
Mapping XS 493c5616
END DESCRIPTION:
XS GIS Cut Line= 5
      1661823.48      6929649.77      1662326.91      6929767.82
      1662618.57      6929818.17      1662842.53      6929701.85
      1663576.80      6929983.06
#Sta/Elev= 30
  4484.0 1823.16  4526.6 1819.99  4557.5 1819.49  4716.9 1824.70  4752.6 1823.54
  4788.9 1820.22  4814.2 1814.22  4849.4 1811.28  4855.3 1809.07  4875.9 1805.35
  4891.8 1799.60  4900.7 1799.28  4917.0 1797.36  4934.3 1799.06  4968.3 1797.64
  4981.8 1790.93  4991.7 1789.54  4992.2 1789.04  5003.3 1789.54  5019.4 1789.91
  5039.7 1793.54  5080.3 1795.22  5147.7 1796.37  5232.3 1795.80  5283.3 1795.28
  5303.5 1793.53  5336.8 1794.96  5746.7 1799.76  5770.7 1800.19  6335.7 1807.64
#Mann=9,-1,0
  4484.0    0.07       0  4788.9   0.035       0  4900.7    0.07       0
  4991.7    0.07       0  5003.3    0.07       0  5232.3   0.035       0
  5336.8    0.07       0  5746.7   0.035       0  5770.7    0.07       0
Bank Sta=4991.7,5003.3
Exp/Cntr=0.3,0.1

Type RM Length L Ch R = 1,19051,345,345,345
BEGIN DESCRIPTION:
Mapping XS 93a1164d
END DESCRIPTION:
XS GIS Cut Line= 3
      1661572.32      6930058.35      1662084.49      6930159.05
      1662354.82      6930208.55
#Sta/Elev= 30
  4478.4 1816.12  4499.4 1814.79  4504.5 1813.73  4532.1 1812.67  4572.9 1809.83
  4583.0 1809.59  4602.2 1808.10  4613.6 1806.65  4644.2 1804.78  4685.0 1803.48
  4725.7 1800.66  4801.4 1797.97  4888.8 1794.46  4909.2 1794.17  4949.9 1791.24
  4960.1 1789.37  4972.2 1788.18  4990.7 1787.89  5018.5 1786.52  5019.0 1786.02
  5029.7 1786.02  5030.2 1786.52  5031.4 1788.96  5041.6 1791.92  5077.5 1793.87
  5088.1 1793.91  5091.6 1793.97  5102.6 1794.41  5122.9 1794.03  5275.2 1793.95
#Mann=6,-1,0
  4478.4    0.07       0  4801.4   0.035       0  5018.5   0.035       0
  5030.2   0.035       0  5088.1    0.07       0  5091.6   0.035       0
Bank Sta=5018.5,5030.2
Exp/Cntr=0.3,0.1