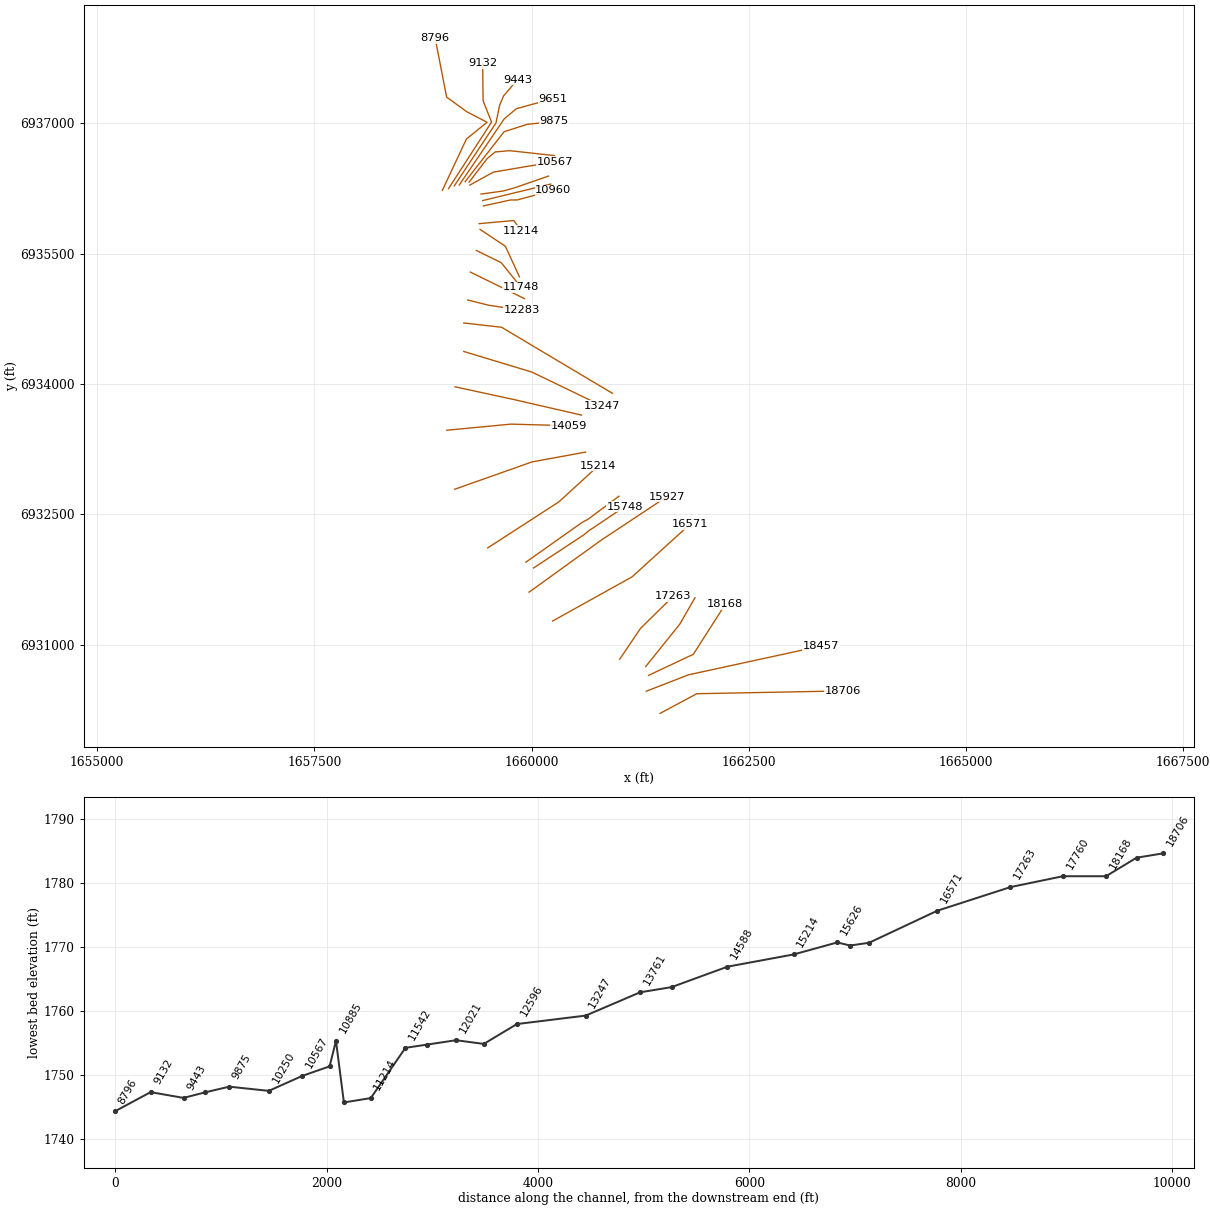
HEC-RAS study Chimney Creek 1097.prj: Chimney Creek 1097 Base Level Engineering

--- Chimney Creek 1097.g01 (geometry) --- (continued)

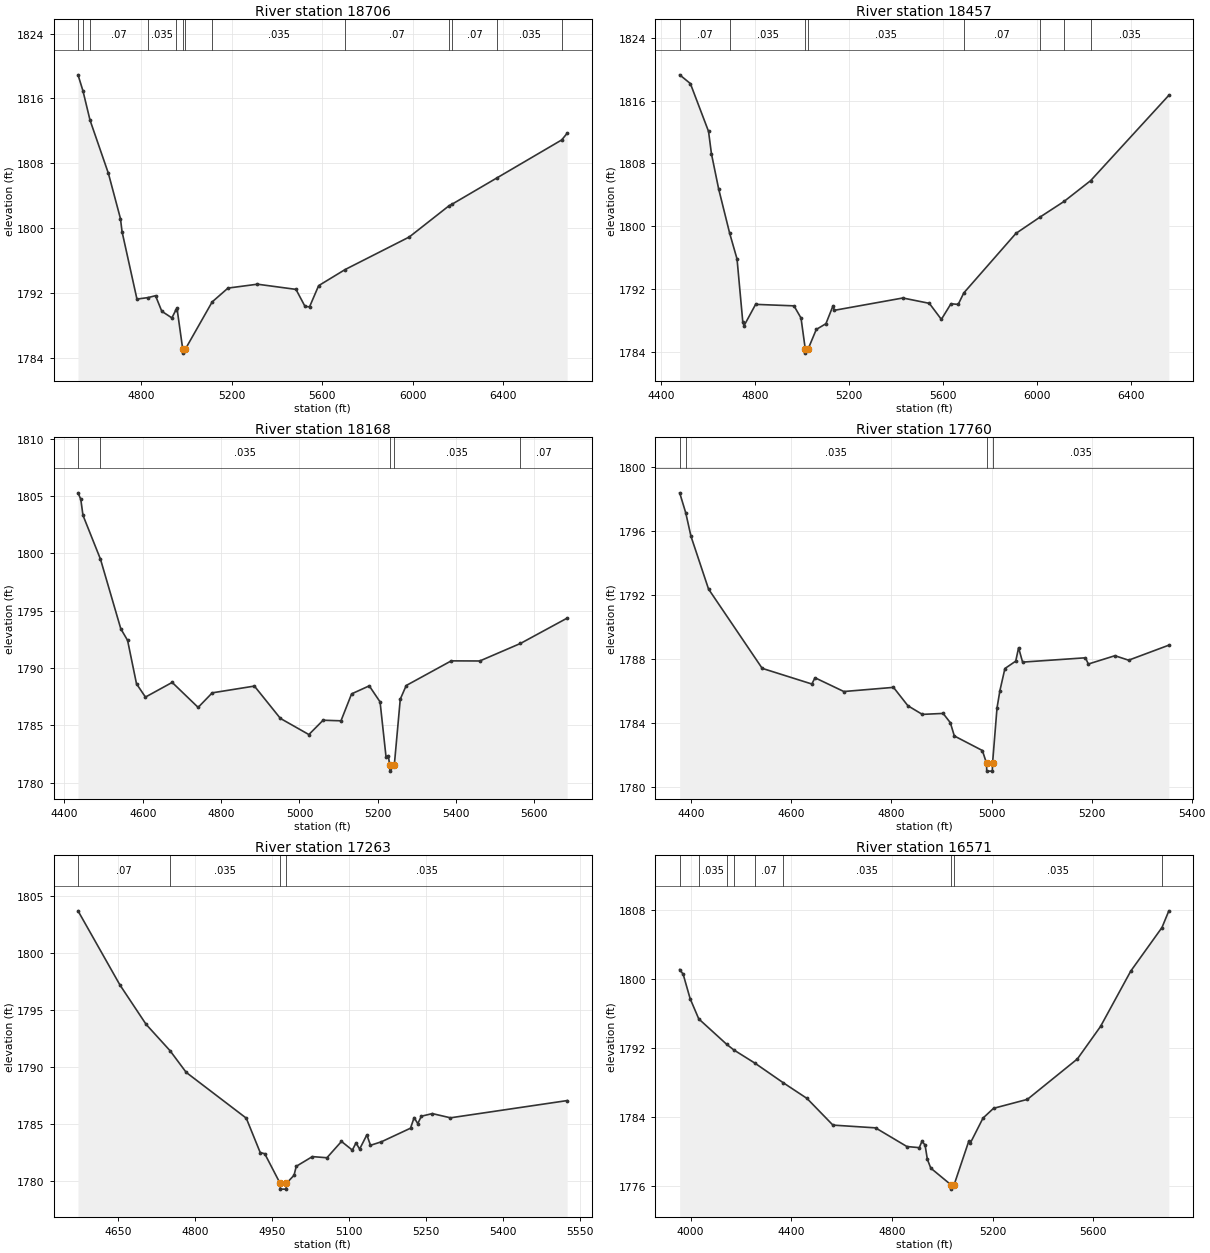
Type RM Length L Ch R = 1,18706,249,249,249
BEGIN DESCRIPTION:
Mapping XS c13191c5
END DESCRIPTION:
XS GIS Cut Line= 3
      1661479.86      6930210.44      1661901.42      6930436.66
      1663581.79      6930468.82
#Sta/Elev= 30
  4522.3 1818.92  4543.9 1816.97  4575.4 1813.32  4656.6 1806.74  4709.7 1801.17
  4716.7 1799.56  4782.5 1791.23  4831.8 1791.42  4864.5 1791.65  4892.1 1789.73
  4936.7 1788.91  4955.3 1789.94  4959.4 1790.08  4984.5 1785.06  4985.0 1784.56
  4996.2 1785.06  5114.4 1790.88  5184.3 1792.59  5314.4 1793.07  5484.4 1792.43
  5524.4 1790.32  5544.4 1790.28  5584.4 1792.89  5701.4 1794.88  5984.5 1798.90
  6160.2 1802.76  6174.1 1802.96  6373.6 1806.23  6657.2 1810.88  6681.4 1811.71
#Mann=13,-1,0
  4522.3    0.07       0  4543.9   0.035       0  4575.4    0.07       0
  4831.8   0.035       0  4955.3    0.07       0  4984.5    0.07       0
  4996.2    0.07       0  5114.4   0.035       0  5701.4    0.07       0
  6160.2   0.035       0  6174.1    0.07       0  6373.6   0.035       0
  6657.2    0.07       0
Bank Sta=4984.5,4996.2
Exp/Cntr=0.3,0.1

Type RM Length L Ch R = 1,18457,289,289,289
BEGIN DESCRIPTION:
Mapping XS 1a37a1dc
END DESCRIPTION:
XS GIS Cut Line= 3
      1661320.49      6930465.37      1661806.36      6930654.11
      1663330.89      6930985.15
#Sta/Elev= 30
  4480.2 1819.27  4525.7 1818.16  4603.0 1812.08  4615.4 1809.23  4646.0 1804.77
  4692.9 1799.13  4724.3 1795.85  4748.9 1787.80  4754.2 1787.38  4803.3 1790.09
  4966.6 1789.90  4996.5 1788.35  5014.7 1784.39  5015.2 1783.89  5026.4 1784.39
  5061.4 1786.90  5102.4 1787.63  5132.8 1789.92  5137.9 1789.33  5429.8 1790.90
  5542.4 1790.22  5593.6 1788.18  5634.5 1790.17  5665.2 1790.08  5689.0 1791.54
  5910.8 1799.11  6015.2 1801.22  6115.9 1803.18  6228.9 1805.82  6561.5 1816.67
#Mann=8,-1,0
  4480.2    0.07       0  4692.9   0.035       0  5014.7   0.035       0
  5026.4   0.035       0  5689.0    0.07       0  6015.2   0.035       0
  6115.9    0.07       0  6228.9   0.035       0
Bank Sta=5014.7,5026.4
Exp/Cntr=0.3,0.1

Type RM Length L Ch R = 1,18168,408,408,408
BEGIN DESCRIPTION:
Mapping XS aa635f51
END DESCRIPTION:
XS GIS Cut Line= 3
      1661347.46      6930648.12      1661861.81      6930890.32
      1662228.51      6931463.78
#Sta/Elev= 30
  4434.5 1805.28  4441.6 1804.72  4447.2 1803.32  4491.9 1799.49  4543.8 1793.42
  4561.1 1792.41  4583.9 1788.62  4606.7 1787.46  4675.0 1788.74  4741.3 1786.56
  4777.3 1787.83  4885.0 1788.42  4951.3 1785.60  5024.1 1784.19  5060.4 1785.44
  5106.1 1785.39  5133.2 1787.74  5178.3 1788.44  5205.9 1787.04  5221.1 1782.25
  5227.1 1782.35  5230.4 1781.50  5230.9 1781.00  5242.2 1781.50  5257.5 1787.28
  5272.7 1788.47  5387.7 1790.62  5460.5 1790.61  5564.5 1792.14  5683.7 1794.35
#Mann=5,-1,0
  4434.5    0.07       0  4491.9   0.035       0  5230.4   0.035       0
  5242.2   0.035       0  5564.5    0.07       0
Bank Sta=5230.4,5242.2
Exp/Cntr=0.3,0.1

Type RM Length L Ch R = 1,17760,497,497,497
BEGIN DESCRIPTION:
Mapping XS 76a57dbb
END DESCRIPTION:
XS GIS Cut Line= 3
      1661313.30      6930748.71      1661705.02      6931235.92
      1661880.93      6931541.33
#Sta/Elev= 30
  4376.8 1798.41  4389.0 1797.15  4399.3 1795.70  4434.5 1792.39  4541.7 1787.43
  4640.9 1786.45  4647.3 1786.84  4704.9 1785.98  4804.1 1786.24  4832.9 1785.09
  4861.7 1784.55  4903.3 1784.61  4917.7 1784.03  4925.7 1783.20  4981.7 1782.29
  4990.0 1781.50  4990.5 1781.00  5001.6 1781.00  5002.1 1781.50  5011.0 1784.95
  5016.8 1786.04  5026.8 1787.42  5048.4 1787.88  5054.1 1788.72  5062.1 1787.82
  5187.7 1788.09  5193.5 1787.70  5246.6 1788.22  5274.0 1787.94  5354.4 1788.88
#Mann=4,-1,0
  4376.8    0.07       0  4389.0   0.035       0  4990.0   0.035       0
  5002.1   0.035       0
Bank Sta=4990,5002.1
Exp/Cntr=0.3,0.1

Type RM Length L Ch R = 1,17263,692,692,692
BEGIN DESCRIPTION:
Mapping XS 9147f174
END DESCRIPTION:
XS GIS Cut Line= 3
      1661014.92      6930834.45      1661254.71      6931189.26
      1661627.95      6931555.99
#Sta/Elev= 30
  4572.8 1803.69  4654.4 1797.19  4705.3 1793.74  4751.7 1791.44  4783.3 1789.53
  4900.1 1785.52  4927.2 1782.51  4936.1 1782.40  4966.0 1779.80  4966.5 1779.30
  4977.6 1779.30  4978.1 1779.80  4993.1 1780.52  4997.3 1781.30  5028.7 1782.15
  5057.0 1782.05  5085.3 1783.48  5106.4 1782.72  5113.6 1783.35  5120.6 1782.81
  5134.7 1784.06  5141.7 1783.14  5163.0 1783.45  5219.6 1784.64  5226.6 1785.57
  5233.7 1785.04  5240.7 1785.69  5262.0 1785.92  5297.3 1785.55  5524.3 1787.06
#Mann=4,-1,0
  4572.8    0.07       0  4751.7   0.035       0  4966.0   0.035       0
  4978.1   0.035       0
Bank Sta=4966,4978.1
Exp/Cntr=0.3,0.1

Type RM Length L Ch R = 1,16571,644,644,644
BEGIN DESCRIPTION:
Mapping XS 253eb35c
END DESCRIPTION:
XS GIS Cut Line= 3
      1660242.82      6931273.22      1661156.45      6931781.04
      1661821.33      6932385.28
#Sta/Elev= 30
  3956.5 1801.13  3970.4 1800.58  3998.1 1797.74  4032.4 1795.39  4144.0 1792.42
  4171.4 1791.79  4255.5 1790.25  4367.1 1787.99  4462.4 1786.15  4565.4 1783.05
  4734.7 1782.73  4859.4 1780.56  4908.6 1780.43  4918.9 1781.15  4931.5 1780.75
  4940.6 1779.08  4954.3 1778.05  5034.6 1776.11  5035.1 1775.61  5046.9 1776.11
  5105.0 1781.16  5111.7 1780.98  5161.7 1783.86  5203.6 1785.00  5338.1 1786.04
  5536.8 1790.74  5628.7 1794.51  5748.9 1800.95  5872.9 1806.01  5900.2 1807.95
#Mann=9,-1,0
  3956.5    0.07       0  4032.4   0.035       0  4144.0    0.07       0
  4171.4   0.035       0  4255.5    0.07       0  4367.1   0.035       0
  5034.6   0.035       0  5046.9   0.035       0  5872.9    0.07       0
Bank Sta=5034.6,5046.9
Exp/Cntr=0.3,0.1

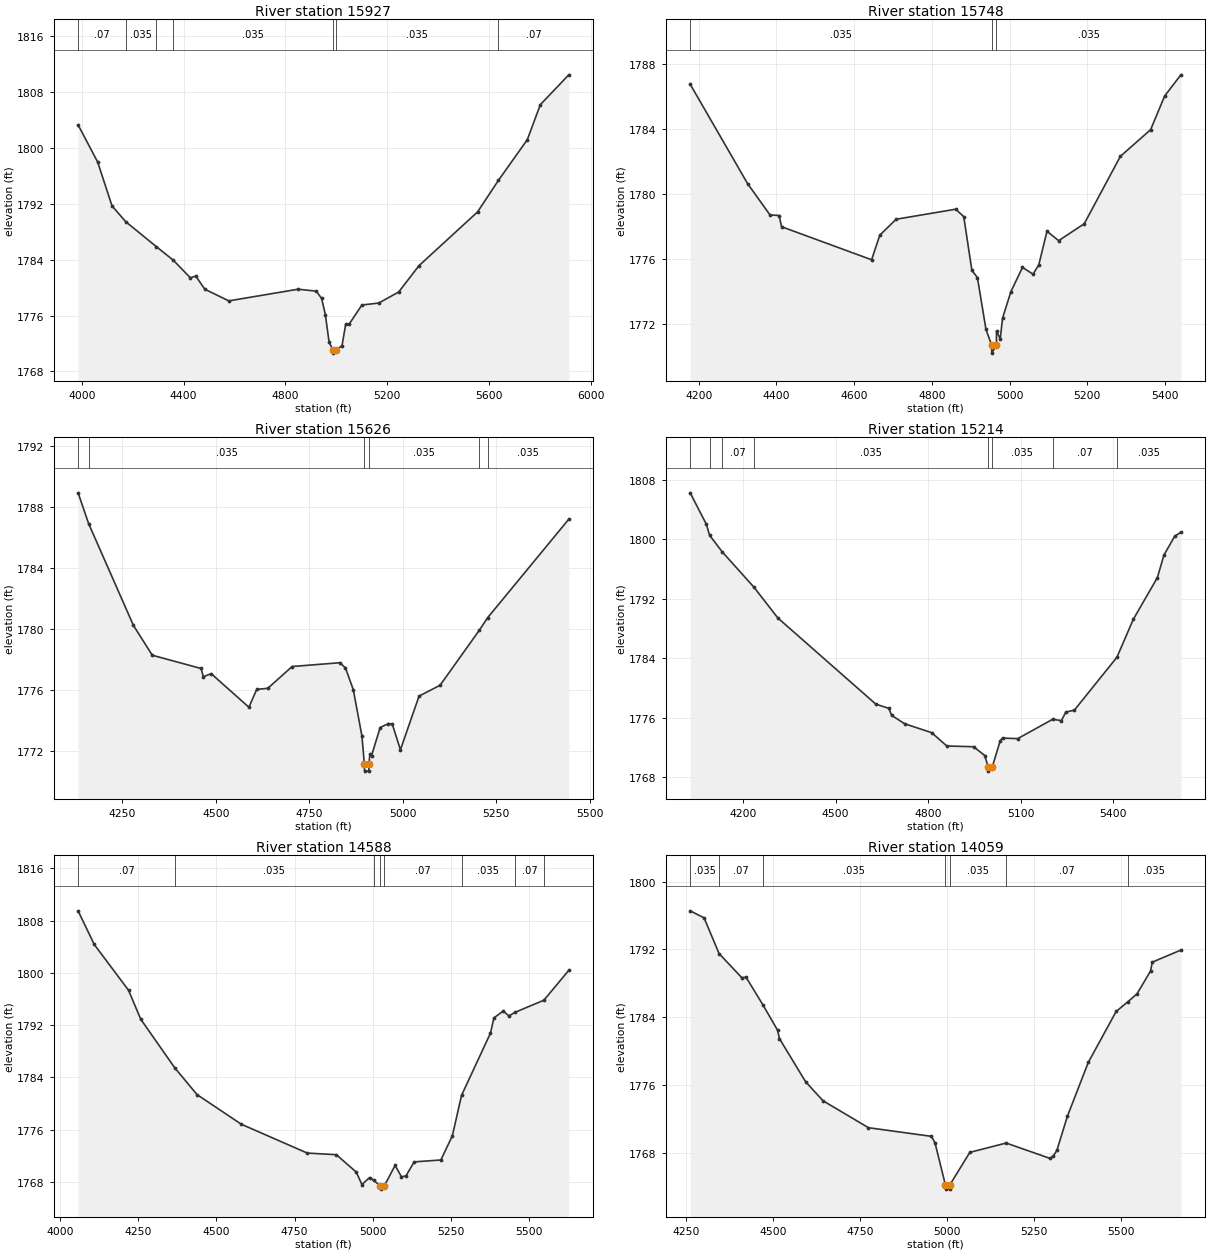
Type RM Length L Ch R = 1,15927,179,179,179
BEGIN DESCRIPTION:
Mapping XS 0fc1e65c
END DESCRIPTION:
XS GIS Cut Line= 3
      1659971.54      6931605.25      1660796.21      6932199.87
      1661555.46      6932703.15
#Sta/Elev= 30
  3985.7 1803.30  4062.6 1797.98  4119.0 1791.70  4172.7 1789.44  4293.7 1785.85
  4360.2 1783.91  4427.0 1781.39  4447.9 1781.66  4483.5 1779.77  4577.9 1778.10
  4850.3 1779.77  4921.5 1779.49  4942.4 1778.45  4957.1 1776.14  4971.8 1772.18
  4986.5 1771.12  4987.0 1770.62  4998.9 1771.12  5022.5 1771.67  5036.9 1774.74
  5049.6 1774.72  5100.7 1777.51  5166.9 1777.79  5245.1 1779.37  5324.9 1783.14
  5554.9 1790.83  5636.9 1795.35  5750.5 1801.18  5801.6 1806.19  5913.3 1810.46
#Mann=7,-1,0
  3985.7    0.07       0  4172.7   0.035       0  4293.7    0.07       0
  4360.2   0.035       0  4986.5   0.035       0  4998.9   0.035       0
  5636.9    0.07       0
Bank Sta=4986.5,4998.9
Exp/Cntr=0.3,0.1

Type RM Length L Ch R = 1,15748,122,122,122
BEGIN DESCRIPTION:
Mapping XS c379b223
END DESCRIPTION:
XS GIS Cut Line= 5
      1660023.57      6931883.77      1660599.12      6932262.70
      1660672.04      6932322.59      1660704.59      6932342.13
      1661070.89      6932588.92
#Sta/Elev= 30
  4178.0 1786.78  4325.7 1780.65  4383.3 1778.72  4407.1 1778.68  4413.1 1777.99
  4645.0 1775.95  4666.1 1777.47  4708.2 1778.45  4861.6 1779.07  4882.2 1778.61
  4903.1 1775.30  4917.4 1774.85  4939.4 1771.65  4953.9 1770.69  4954.4 1770.19
  4966.3 1770.69  4966.5 1771.55  4976.2 1771.07  4982.0 1772.34  5003.5 1773.98
  5033.4 1775.48  5060.5 1775.06  5075.4 1775.64  5096.4 1777.71  5126.4 1777.13
  5192.3 1778.17  5285.3 1782.33  5363.3 1783.98  5399.3 1786.05  5441.1 1787.36
#Mann=3,-1,0
  4178.0   0.035       0  4953.9   0.035       0  4966.3   0.035       0
Bank Sta=4953.9,4966.3
Exp/Cntr=0.3,0.1

Type RM Length L Ch R = 1,15626,412,412,412
BEGIN DESCRIPTION:
Mapping XS 5c9452f6
END DESCRIPTION:
XS GIS Cut Line= 4
      1659935.09      6931950.22      1660576.99      6932404.63
      1660651.21      6932444.99      1661005.39      6932709.33
#Sta/Elev= 30
  4131.2 1788.92  4159.8 1786.88  4279.4 1780.22  4329.8 1778.27  4460.3 1777.40
  4466.4 1776.86  4487.3 1777.06  4588.3 1774.86  4609.2 1776.03  4638.7 1776.10
  4704.0 1777.53  4832.0 1777.78  4846.7 1777.43  4867.6 1776.01  4890.7 1772.97
  4897.1 1771.17  4897.6 1770.67  4909.0 1770.67  4909.5 1771.17  4912.0 1771.79
  4916.3 1771.68  4939.5 1773.53  4961.4 1773.79  4971.8 1773.76  4993.7 1772.07
  5043.5 1775.59  5099.8 1776.30  5204.5 1779.90  5227.3 1780.74  5444.1 1787.19
#Mann=6,-1,0
  4131.2    0.07       0  4159.8   0.035       0  4897.1   0.035       0
  4909.5   0.035       0  5204.5    0.07       0  5227.3   0.035       0
Bank Sta=4897.1,4909.5
Exp/Cntr=0.3,0.1

Type RM Length L Ch R = 1,15214,626,626,626
BEGIN DESCRIPTION:
Mapping XS dae7dea8
END DESCRIPTION:
XS GIS Cut Line= 3
      1659496.14      6932114.71      1660314.26      6932644.21
      1660769.98      6933060.87
#Sta/Elev= 30
  4028.3 1806.22  4080.5 1802.01  4091.4 1800.51  4131.5 1798.32  4235.4 1793.52
  4312.8 1789.39  4630.5 1777.81  4672.7 1777.24  4681.9 1776.30  4724.1 1775.17
  4811.9 1773.97  4860.8 1772.18  4947.7 1772.08  4984.0 1770.90  4995.5 1769.30
  4996.0 1768.80  5007.9 1769.30  5034.2 1772.89  5041.6 1773.24  5090.9 1773.17
  5204.3 1775.77  5232.8 1775.59  5247.0 1776.74  5274.8 1777.00  5412.9 1784.12
  5465.9 1789.21  5544.2 1794.83  5565.2 1797.84  5600.3 1800.39  5620.3 1800.91
#Mann=8,-1,0
  4028.3    0.07       0  4091.4   0.035       0  4131.5    0.07       0
  4235.4   0.035       0  4995.5   0.035       0  5007.9   0.035       0
  5204.3    0.07       0  5412.9   0.035       0
Bank Sta=4995.5,5007.9
Exp/Cntr=0.3,0.1

Type RM Length L Ch R = 1,14588,529,529,529
BEGIN DESCRIPTION:
Mapping XS e2b00b57
END DESCRIPTION:
XS GIS Cut Line= 3
      1659116.37      6932789.62      1660006.10      6933104.28
      1660621.24      6933216.91
#Sta/Elev= 30
  4057.4 1809.49  4109.0 1804.35  4218.9 1797.32  4257.5 1792.92  4366.4 1785.47
  4437.8 1781.36  4579.2 1776.83  4790.2 1772.41  4883.3 1772.16  4946.9 1769.50
  4965.1 1767.59  4989.4 1768.66  5002.1 1768.25  5024.2 1767.39  5024.7 1766.89
  5036.9 1767.39  5071.2 1770.53  5091.5 1768.77  5105.9 1768.92  5132.2 1771.06
  5217.4 1771.35  5254.2 1775.04  5283.5 1781.23  5376.2 1790.78  5387.1 1793.10
  5416.8 1794.14  5435.2 1793.41  5454.6 1793.95  5547.0 1795.81  5626.5 1800.38
#Mann=8,-1,0
  4057.4    0.07       0  4366.4   0.035       0  5002.1    0.07       0
  5024.2   0.035       0  5036.9    0.07       0  5283.5   0.035       0
  5454.6    0.07       0  5547.0   0.035       0
Bank Sta=5024.2,5036.9
Exp/Cntr=0.3,0.1

Type RM Length L Ch R = 1,14059,298,298,298
BEGIN DESCRIPTION:
Mapping XS f95a88b3
END DESCRIPTION:
XS GIS Cut Line= 3
      1659025.28      6933468.62      1659762.30      6933538.94
      1660430.79      6933520.73
#Sta/Elev= 30
  4263.0 1796.55  4302.9 1795.72  4345.9 1791.51  4411.4 1788.65  4423.4 1788.72
  4472.6 1785.40  4513.9 1782.46  4519.3 1781.47  4594.2 1776.39  4644.4 1774.13
  4775.0 1770.95  4955.8 1769.93  4965.9 1769.18  4995.9 1764.20  4996.4 1763.70
  5008.1 1763.70  5008.6 1764.20  5066.1 1768.04  5170.4 1769.14  5296.2 1767.33
  5306.2 1767.62  5316.2 1768.30  5346.2 1772.30  5406.2 1778.66  5486.2 1784.67
  5519.9 1785.82  5546.3 1786.76  5585.0 1789.45  5590.0 1790.49  5672.1 1791.92
#Mann=7,-1,0
  4263.0   0.035       0  4345.9    0.07       0  4472.6   0.035       0
  4995.9   0.035       0  5008.6   0.035       0  5170.4    0.07       0
  5519.9   0.035       0
Bank Sta=4995.9,5008.6
Exp/Cntr=0.3,0.1

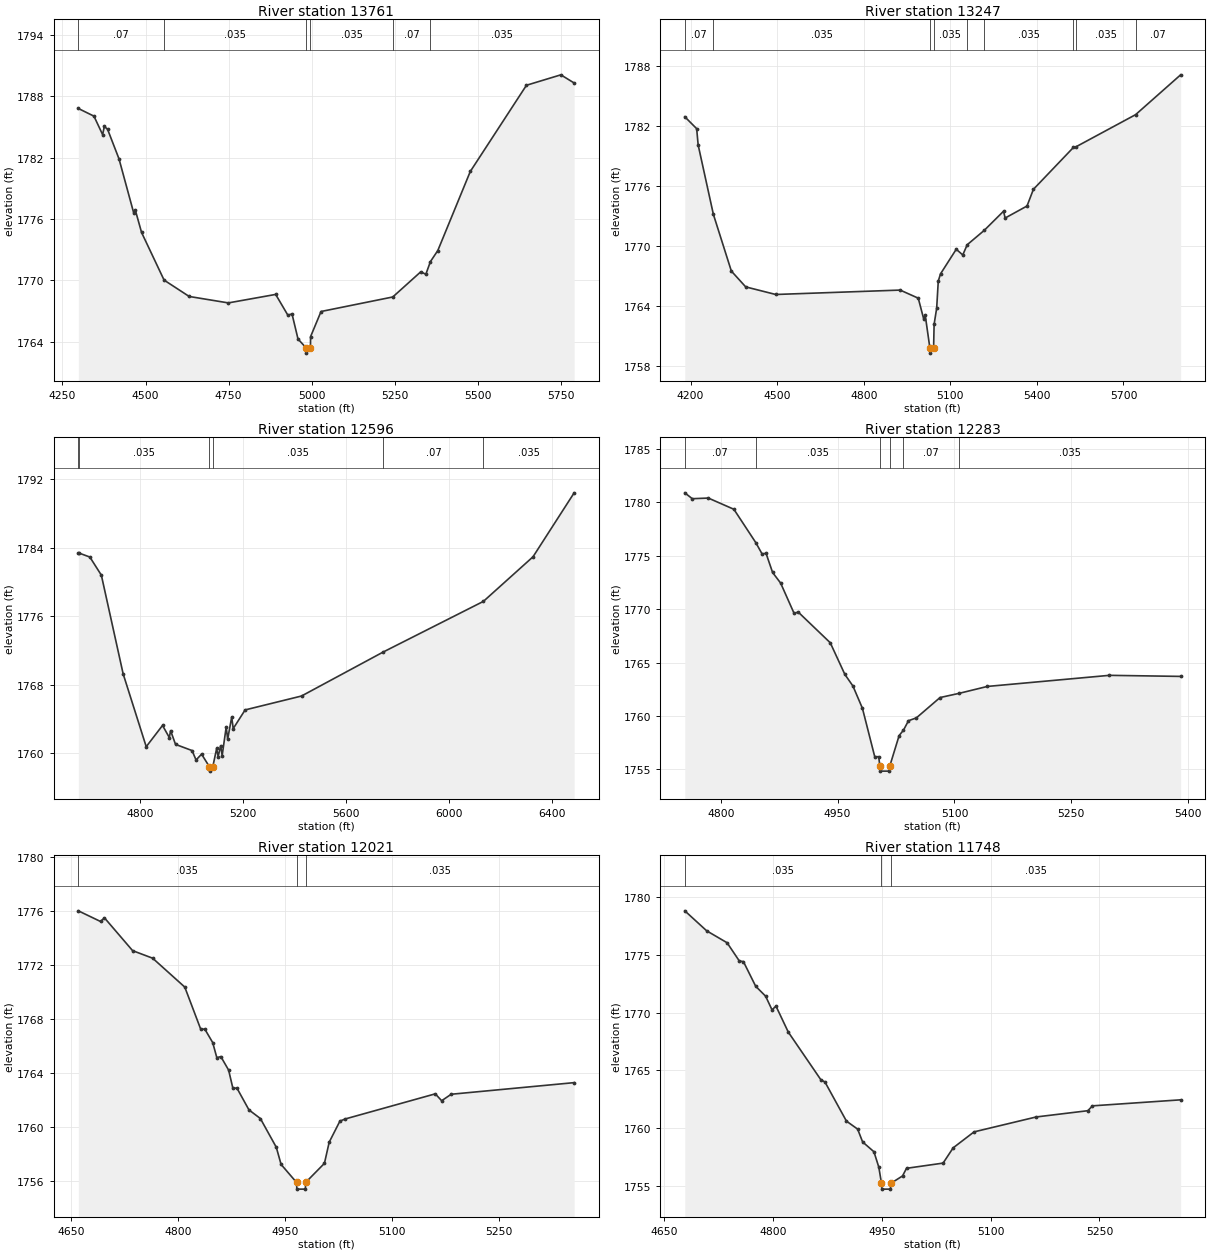
Type RM Length L Ch R = 1,13761,514,514,514
BEGIN DESCRIPTION:
Mapping XS f0a5c2aa
END DESCRIPTION:
XS GIS Cut Line= 3
      1659119.11      6933968.61      1659803.96      6933820.19
      1660574.83      6933643.09
#Sta/Elev= 30
  4297.8 1786.81  4344.8 1786.06  4370.9 1784.25  4376.0 1785.05  4385.7 1784.78
  4420.1 1781.89  4464.2 1776.62  4469.3 1776.87  4488.0 1774.69  4555.8 1770.03
  4631.3 1768.43  4749.1 1767.80  4891.5 1768.63  4928.0 1766.61  4940.7 1766.72
  4958.7 1764.27  4983.5 1763.39  4984.0 1762.89  4996.2 1763.39  4996.5 1764.50
  5028.0 1766.96  5243.8 1768.38  5328.0 1770.84  5343.3 1770.60  5357.1 1771.84
  5379.3 1772.92  5477.0 1780.65  5646.0 1789.08  5749.5 1790.10  5789.5 1789.30
#Mann=6,-1,0
  4297.8    0.07       0  4555.8   0.035       0  4983.5   0.035       0
  4996.2   0.035       0  5243.8    0.07       0  5357.1   0.035       0
Bank Sta=4983.5,4996.2
Exp/Cntr=0.3,0.1

Type RM Length L Ch R = 1,13247,651,651,651
BEGIN DESCRIPTION:
Mapping XS 5db07356
END DESCRIPTION:
XS GIS Cut Line= 3
      1659220.64      6934374.87      1660004.48      6934137.89
      1660814.42      6933747.25
#Sta/Elev= 30
  4180.0 1782.88  4221.1 1781.69  4226.3 1780.06  4279.0 1773.13  4341.3 1767.46
  4391.0 1765.88  4495.1 1765.12  4926.3 1765.56  4989.0 1764.75  5007.6 1762.70
  5013.1 1763.05  5029.3 1759.76  5029.8 1759.26  5042.1 1759.76  5043.9 1762.14
  5052.8 1763.75  5058.3 1766.46  5066.1 1767.18  5120.6 1769.64  5143.2 1769.07
  5158.6 1770.09  5217.7 1771.53  5284.5 1773.44  5290.0 1772.76  5365.8 1773.96
  5388.0 1775.63  5526.5 1779.81  5535.6 1779.88  5742.1 1783.09  5898.1 1787.07
#Mann=9,-1,0
  4180.0    0.07       0  4279.0   0.035       0  5029.3   0.035       0
  5042.1   0.035       0  5158.6    0.07       0  5217.7   0.035       0
  5526.5    0.07       0  5535.6   0.035       0  5742.1    0.07       0
Bank Sta=5029.3,5042.1
Exp/Cntr=0.3,0.1

Type RM Length L Ch R = 1,12596,313,313,313
BEGIN DESCRIPTION:
Mapping XS 1619a261
END DESCRIPTION:
XS GIS Cut Line= 3
      1659220.65      6934703.00      1659655.52      6934653.52
      1660930.78      6933893.57
#Sta/Elev= 30
  4561.9 1783.36  4566.0 1783.36  4606.5 1782.91  4651.1 1780.80  4735.6 1769.29
  4825.1 1760.79  4888.3 1763.27  4914.6 1761.86  4919.6 1762.66  4938.7 1761.06
  5002.7 1760.34  5018.3 1759.24  5039.7 1759.92  5070.3 1758.44  5070.8 1757.94
  5083.1 1758.44  5098.1 1760.58  5103.9 1759.64  5113.7 1760.91  5119.5 1759.75
  5135.1 1763.08  5140.9 1761.68  5156.5 1764.25  5162.3 1762.90  5208.5 1765.08
  5427.1 1766.70  5744.3 1771.84  6132.3 1777.74  6324.6 1782.94  6484.1 1790.40
#Mann=6,-1,0
  4561.9    0.07       0  4566.0   0.035       0  5070.3   0.035       0
  5083.1   0.035       0  5744.3    0.07       0  6132.3   0.035       0
Bank Sta=5070.3,5083.1
Exp/Cntr=0.3,0.1

Type RM Length L Ch R = 1,12283,262,262,262
BEGIN DESCRIPTION:
Mapping XS 5e245788
END DESCRIPTION:
XS GIS Cut Line= 3
      1659265.67      6934967.49      1659504.38      6934907.82
      1659890.31      6934849.28
#Sta/Elev= 30
  4753.9 1780.90  4763.5 1780.35  4784.1 1780.41  4816.9 1779.36  4845.0 1776.24
  4853.0 1775.19  4858.2 1775.23  4866.6 1773.44  4876.9 1772.45  4894.2 1769.61
  4899.4 1769.74  4940.6 1766.86  4959.4 1763.89  4969.7 1762.81  4981.9 1760.72
  4997.7 1756.19  5002.8 1756.19  5004.2 1755.34  5004.7 1754.84  5016.6 1754.84
  5017.1 1755.34  5029.0 1758.17  5034.6 1758.68  5041.0 1759.56  5051.2 1759.83
  5081.5 1761.73  5105.8 1762.12  5142.2 1762.77  5298.9 1763.81  5390.3 1763.71
#Mann=6,-1,0
  4753.9    0.07       0  4845.0   0.035       0  5004.2   0.035       0
  5017.1   0.035       0  5034.6    0.07       0  5105.8   0.035       0
Bank Sta=5004.2,5017.1
Exp/Cntr=0.3,0.1

Type RM Length L Ch R = 1,12021,273,273,273
BEGIN DESCRIPTION:
Mapping XS e34adf55
END DESCRIPTION:
XS GIS Cut Line= 3
      1659296.09      6935288.66      1659600.95      6935138.94
      1659919.63      6934982.83
#Sta/Elev= 30
  4660.4 1776.04  4691.5 1775.25  4697.0 1775.52  4736.4 1773.09  4764.5 1772.53
  4809.5 1770.39  4831.9 1767.26  4837.5 1767.28  4848.6 1766.28  4854.4 1765.16
  4860.0 1765.24  4870.9 1764.24  4876.9 1762.89  4882.5 1762.91  4899.4 1761.29
  4915.4 1760.65  4937.7 1758.52  4944.4 1757.25  4966.0 1755.92  4966.5 1755.42
  4978.4 1755.42  4978.9 1755.92  5005.1 1757.33  5011.8 1758.90  5026.8 1760.46
  5034.3 1760.62  5160.4 1762.48  5169.3 1761.97  5182.7 1762.45  5354.9 1763.31
#Mann=3,-1,0
  4660.4   0.035       0  4966.0   0.035       0  4978.9   0.035       0
Bank Sta=4966,4978.9
Exp/Cntr=0.3,0.1

Type RM Length L Ch R = 1,11748,206,206,206
BEGIN DESCRIPTION:
Mapping XS 2850c039
END DESCRIPTION:
XS GIS Cut Line= 3
      1659364.99      6935537.36      1659651.42      6935396.75
      1659879.97      6935113.03
#Sta/Elev= 30
  4678.5 1778.80  4708.7 1777.07  4736.8 1776.04  4753.7 1774.46  4759.3 1774.41
  4776.2 1772.28  4789.9 1771.42  4798.7 1770.24  4804.2 1770.56  4821.1 1768.32
  4866.1 1764.19  4871.7 1764.00  4901.3 1760.62  4916.7 1759.93  4923.6 1758.82
  4939.2 1757.97  4945.9 1756.64  4949.6 1755.24  4950.1 1754.74  4962.0 1754.74
  4962.5 1755.24  4978.6 1755.88  4984.1 1756.54  5034.5 1756.99  5048.4 1758.31
  5077.2 1759.69  5162.9 1760.98  5234.0 1761.52  5240.4 1761.94  5361.9 1762.46
#Mann=3,-1,0
  4678.5   0.035       0  4949.6   0.035       0  4962.5   0.035       0
Bank Sta=4949.6,4962.5
Exp/Cntr=0.3,0.1

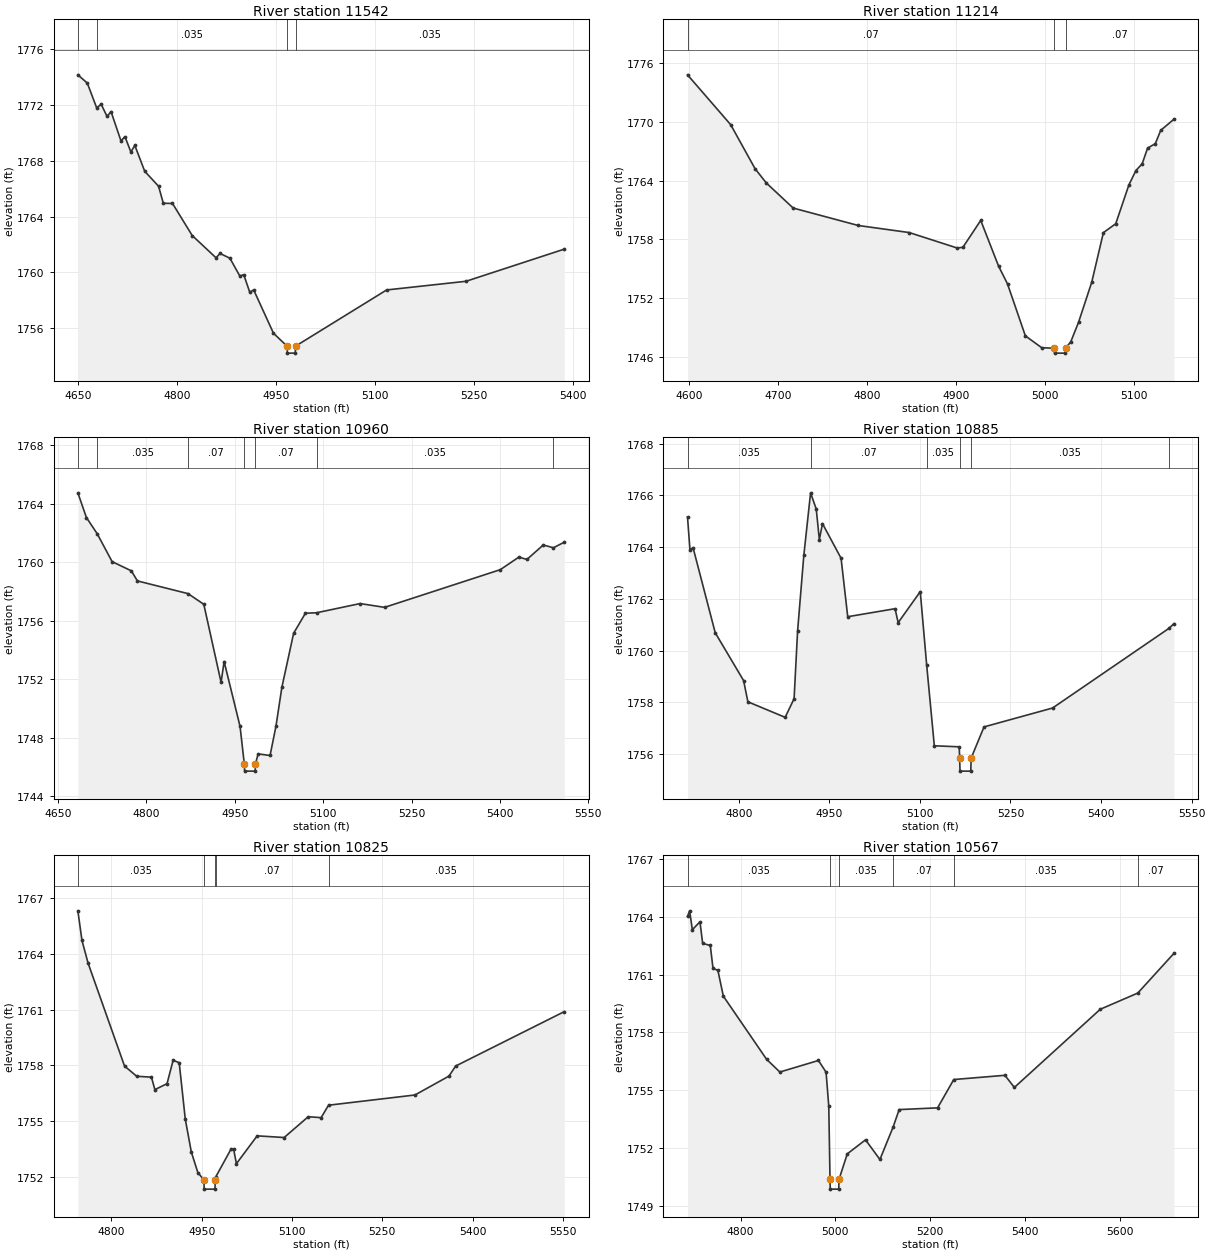
Type RM Length L Ch R = 1,11542,328,328,328
BEGIN DESCRIPTION:
Mapping XS cbd5e704
END DESCRIPTION:
XS GIS Cut Line= 3
      1659407.20      6935780.29      1659699.19      6935585.69
      1659860.55      6935234.16
#Sta/Elev= 30
  4649.1 1774.14  4663.4 1773.55  4677.7 1771.77  4684.4 1772.04  4693.4 1771.16
  4699.4 1771.51  4714.5 1769.41  4720.5 1769.72  4729.5 1768.62  4735.5 1769.09
  4750.5 1767.24  4771.5 1766.17  4778.7 1764.95  4792.6 1764.94  4822.6 1762.64
  4858.7 1761.05  4864.7 1761.36  4879.7 1761.02  4894.7 1759.75  4900.7 1759.84
  4909.8 1758.59  4915.8 1758.75  4945.8 1755.65  4966.4 1754.73  4966.9 1754.23
  4978.8 1754.23  4979.3 1754.73  5117.4 1758.75  5237.8 1759.37  5386.8 1761.67
#Mann=4,-1,0
  4649.1    0.07       0  4677.7   0.035       0  4966.4   0.035       0
  4979.3   0.035       0
Bank Sta=4966.4,4979.3
Exp/Cntr=0.3,0.1

Type RM Length L Ch R = 1,11214,254,254,254
BEGIN DESCRIPTION:
Chimney Creek 1097 18.0
END DESCRIPTION:
XS GIS Cut Line= 3
      1659396.67      6935845.97      1659796.76      6935881.99
      1659879.99      6935763.01
#Sta/Elev= 30
  4598.3 1774.78  4646.8 1769.70  4674.3 1765.20  4687.0 1763.74  4717.1 1761.19
  4790.3 1759.41  4847.6 1758.69  4901.3 1757.12  4907.9 1757.18  4928.0 1759.93
  4948.0 1755.28  4958.1 1753.45  4978.2 1748.15  4996.6 1746.94  5010.5 1746.89
  5011.0 1746.39  5023.0 1746.39  5023.5 1746.89  5029.3 1747.56  5038.0 1749.54
  5052.8 1753.62  5065.9 1758.68  5079.8 1759.59  5094.6 1763.55  5102.5 1765.02
  5109.5 1765.70  5115.6 1767.30  5124.3 1767.76  5130.4 1769.12  5145.2 1770.25
#Mann=3,-1,0
  4598.3    0.07       0  5010.5    0.07       0  5023.5    0.07       0
Bank Sta=5010.5,5023.5
Exp/Cntr=0.3,0.1

Type RM Length L Ch R = 1,10960,75,75,75
BEGIN DESCRIPTION:
Chimney Creek 1097 16.0
END DESCRIPTION:
XS GIS Cut Line= 4
      1659446.43      6936049.74      1659754.88      6936117.95
      1659836.09      6936119.09      1660249.38      6936229.86
#Sta/Elev= 30
  4684.1 1764.76  4698.6 1763.07  4716.9 1761.96  4742.2 1760.05  4774.8 1759.42
  4785.1 1758.73  4871.0 1757.86  4897.7 1757.13  4927.0 1751.79  4932.2 1753.21
  4959.2 1748.77  4966.4 1746.21  4966.9 1745.71  4984.8 1745.71  4985.3 1746.21
  4989.9 1746.89  5010.1 1746.78  5020.1 1748.78  5030.1 1751.44  5050.1 1755.15
  5070.1 1756.52  5088.9 1756.55  5162.9 1757.18  5204.3 1756.92  5400.6 1759.50
  5432.1 1760.36  5445.8 1760.20  5473.5 1761.19  5490.7 1761.00  5509.1 1761.38
#Mann=7,-1,0
  4684.1    0.07       0  4716.9   0.035       0  4871.0    0.07       0
  4966.4    0.07       0  4985.3    0.07       0  5088.9   0.035       0
  5490.7    0.07       0
Bank Sta=4966.4,4985.3
Exp/Cntr=0.3,0.1

Type RM Length L Ch R = 1,10885,60,60,60
BEGIN DESCRIPTION:
Mapping XS 35edef91
END DESCRIPTION:
XS GIS Cut Line= 3
      1659437.82      6936111.60      1659715.55      6936178.87
      1660220.48      6936301.64
#Sta/Elev= 30
  4715.2 1765.17  4719.3 1763.89  4724.4 1763.98  4761.1 1760.69  4808.1 1758.84
  4815.2 1758.02  4876.9 1757.42  4891.7 1758.14  4897.5 1760.76  4907.8 1763.68
  4919.0 1766.10  4928.4 1765.47  4933.5 1764.29  4938.7 1764.91  4969.5 1763.57
  4980.5 1761.31  5058.9 1761.62  5064.0 1761.08  5100.6 1762.28  5111.2 1759.45
  5123.9 1756.32  5165.1 1756.28  5165.9 1755.84  5166.4 1755.34  5184.3 1755.34
  5184.8 1755.84  5206.2 1757.05  5319.7 1757.78  5512.4 1760.86  5520.6 1761.04
#Mann=6,-1,0
  4715.2   0.035       0  4919.0    0.07       0  5111.2   0.035       0
  5165.9    0.07       0  5184.8   0.035       0  5512.4    0.07       0
Bank Sta=5165.9,5184.8
Exp/Cntr=0.3,0.1

Type RM Length L Ch R = 1,10825,258,258,258
BEGIN DESCRIPTION:
Mapping XS d0fc20fe
END DESCRIPTION:
XS GIS Cut Line= 4
      1659418.25      6936186.46      1659671.06      6936221.18
      1659798.02      6936255.91      1660195.86      6936393.61
#Sta/Elev= 30
  4744.4 1766.33  4751.2 1764.74  4761.3 1763.52  4821.9 1757.97  4842.1 1757.42
  4866.6 1757.37  4872.3 1756.70  4892.5 1757.02  4902.6 1758.28  4912.7 1758.15
  4922.8 1755.11  4932.9 1753.33  4943.7 1752.23  4953.7 1751.84  4954.2 1751.34
  4972.1 1751.34  4972.6 1751.84  4973.1 1751.98  4999.0 1753.51  5003.0 1753.51
  5007.7 1752.71  5042.2 1754.21  5087.0 1754.12  5127.0 1755.24  5148.4 1755.19
  5160.7 1755.86  5304.2 1756.41  5360.8 1757.43  5371.8 1757.97  5552.2 1760.90
#Mann=5,-1,0
  4744.4   0.035       0  4953.7    0.07       0  4972.6   0.035       0
  4973.1    0.07       0  5160.7   0.035       0
Bank Sta=4953.7,4972.6
Exp/Cntr=0.3,0.1

Type RM Length L Ch R = 1,10567,317,317,317
BEGIN DESCRIPTION:
Mapping XS 83ff851c
END DESCRIPTION:
XS GIS Cut Line= 3
      1659288.75      6936289.38      1659561.07      6936439.10
      1660266.61      6936558.28
#Sta/Elev= 30
  4688.0 1764.02  4692.5 1764.31  4698.2 1763.33  4714.3 1763.74  4720.0 1762.62
  4736.1 1762.51  4741.8 1761.32  4752.1 1761.22  4763.6 1759.88  4854.9 1756.60
  4882.9 1755.94  4964.3 1756.54  4980.4 1755.93  4986.1 1754.16  4988.7 1750.36
  4989.2 1749.86  5007.1 1749.86  5007.6 1750.36  5025.1 1751.69  5063.6 1752.42
  5094.0 1751.40  5121.8 1753.08  5134.6 1753.99  5215.7 1754.08  5249.8 1755.55
  5357.7 1755.77  5377.7 1755.14  5559.0 1759.20  5638.1 1760.04  5714.3 1762.10
#Mann=6,-1,0
  4688.0   0.035       0  4988.7   0.035       0  5007.6   0.035       0
  5121.8    0.07       0  5249.8   0.035       0  5638.1    0.07       0
Bank Sta=4988.7,5007.6
Exp/Cntr=0.3,0.1

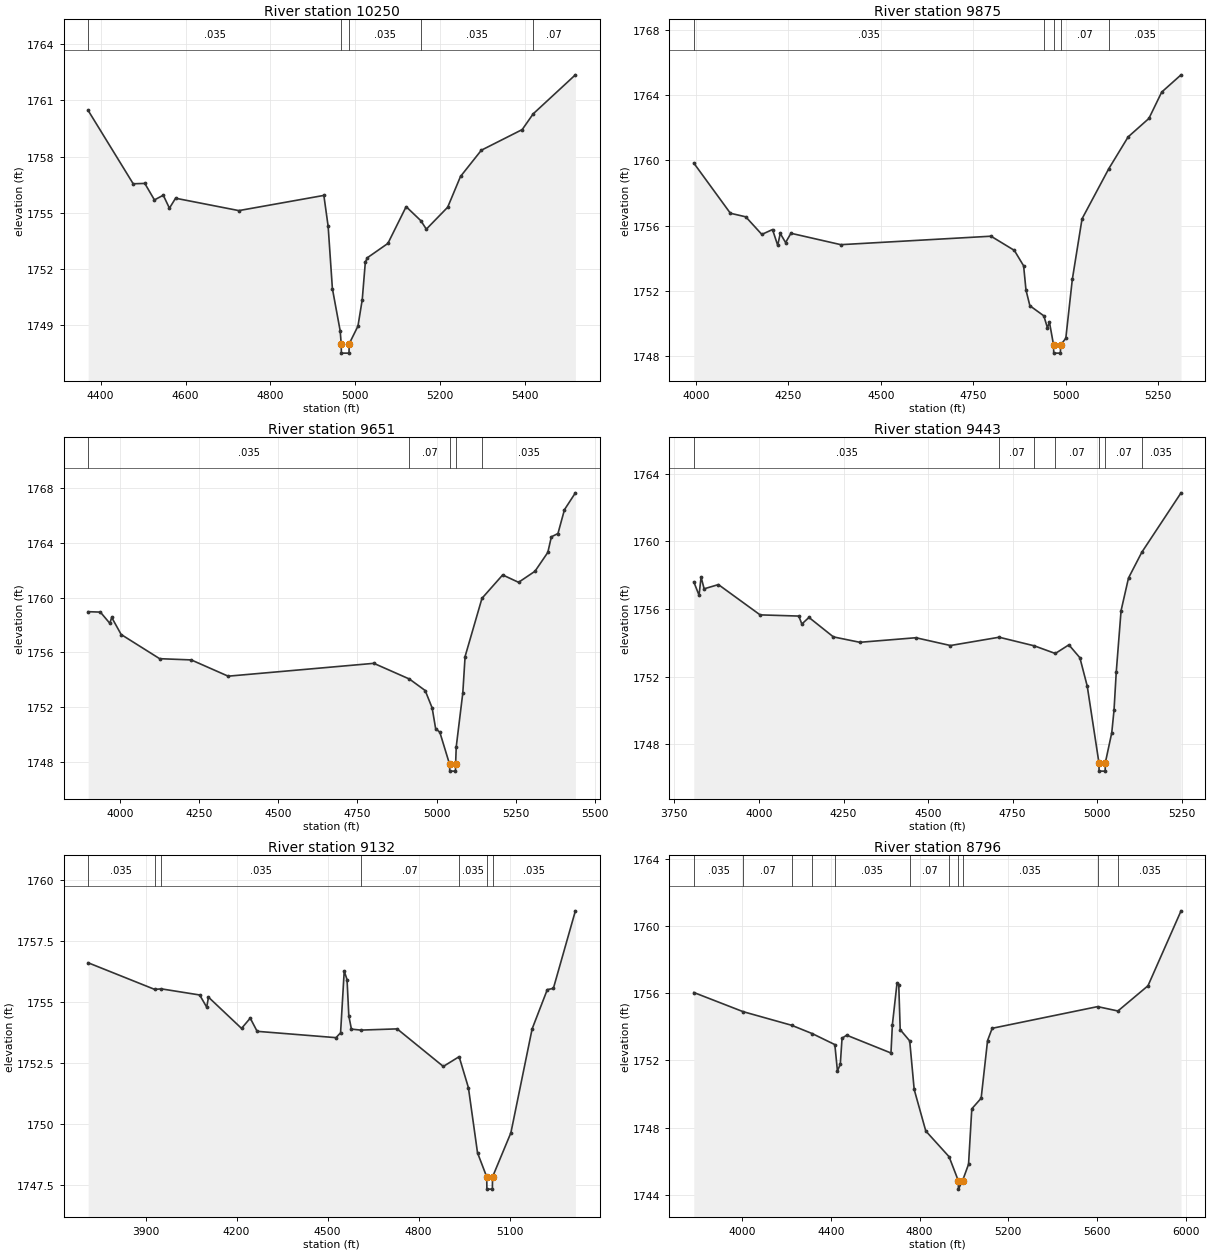
Type RM Length L Ch R = 1,10250,375,375,375
BEGIN DESCRIPTION:
Mapping XS 17a2a819
END DESCRIPTION:
XS GIS Cut Line= 5
      1659281.17      6936323.96      1659491.27      6936596.57
      1659581.55      6936671.22      1659748.90      6936685.81
      1660264.00      6936629.25
#Sta/Elev= 30
  4370.7 1760.46  4476.8 1756.55  4504.1 1756.57  4526.8 1755.69  4547.6 1755.94
  4562.1 1755.25  4576.6 1755.78  4725.6 1755.12  4925.8 1755.93  4935.9 1754.28
  4945.9 1750.96  4964.3 1748.70  4966.6 1748.02  4967.1 1747.52  4985.0 1747.52
  4985.5 1748.02  5006.1 1748.96  5016.2 1750.37  5023.5 1752.38  5028.5 1752.61
  5076.6 1753.37  5119.6 1755.33  5154.3 1754.58  5167.1 1754.13  5217.4 1755.30
  5247.6 1756.94  5296.7 1758.34  5392.9 1759.44  5418.8 1760.28  5518.2 1762.36
#Mann=5,-1,0
  4370.7   0.035       0  4966.6    0.07       0  4985.5   0.035       0
  5154.3   0.035       0  5418.8    0.07       0
Bank Sta=4966.6,4985.5
Exp/Cntr=0.3,0.1

Type RM Length L Ch R = 1,9875,224,224,224
BEGIN DESCRIPTION:
Mapping XS 0985add4
END DESCRIPTION:
XS GIS Cut Line= 4
      1659236.08      6936329.23      1659683.98      6936903.86
      1659947.50      6936988.00      1660256.98      6937022.57
#Sta/Elev= 30
  3994.8 1759.84  4093.6 1756.76  4135.2 1756.54  4178.6 1755.46  4207.5 1755.76
  4221.5 1754.79  4228.4 1755.52  4242.8 1754.96  4257.3 1755.53  4392.1 1754.83
  4797.9 1755.35  4860.9 1754.48  4886.0 1753.53  4892.4 1752.04  4902.9 1751.08
  4940.6 1750.46  4950.4 1749.72  4955.7 1750.08  4966.9 1748.67  4967.4 1748.17
  4985.4 1748.17  4985.9 1748.67  5000.0 1749.08  5017.6 1752.70  5043.9 1756.42
  5116.0 1759.49  5168.5 1761.45  5224.5 1762.58  5259.1 1764.20  5311.4 1765.26
#Mann=5,-1,0
  3994.8   0.035       0  4940.6    0.07       0  4966.9    0.07       0
  4985.9    0.07       0  5116.0   0.035       0
Bank Sta=4966.9,4985.9
Exp/Cntr=0.3,0.1

Type RM Length L Ch R = 1,9651,208,208,208
BEGIN DESCRIPTION:
Mapping XS 0d0e9665
END DESCRIPTION:
XS GIS Cut Line= 4
      1659168.35      6936291.01      1659685.50      6937051.69
      1659825.72      6937168.70      1660248.24      6937285.01
#Sta/Elev= 30
  3898.5 1758.97  3937.1 1758.94  3967.0 1758.12  3973.0 1758.55  4002.9 1757.30
  4124.6 1755.53  4224.5 1755.44  4341.2 1754.25  4801.8 1755.19  4914.4 1754.04
  4964.2 1753.20  4986.3 1751.92  4997.2 1750.42  5010.6 1750.14  5041.4 1747.80
  5041.9 1747.30  5059.9 1747.30  5060.4 1747.80  5062.4 1749.08  5083.2 1753.03
  5090.4 1755.69  5143.8 1759.95  5209.2 1761.66  5259.5 1761.12  5311.4 1761.93
  5352.0 1763.31  5363.2 1764.45  5384.0 1764.69  5404.7 1766.44  5439.2 1767.67
#Mann=5,-1,0
  3898.5   0.035       0  4914.4    0.07       0  5041.4    0.07       0
  5060.4    0.07       0  5143.8   0.035       0
Bank Sta=5041.4,5060.4
Exp/Cntr=0.3,0.1

Type RM Length L Ch R = 1,9443,311,311,311
BEGIN DESCRIPTION:
Mapping XS 8cb56456
END DESCRIPTION:
XS GIS Cut Line= 5
      1659111.07      6936280.61      1659591.07      6937005.47
      1659631.81      6937205.91      1659678.00      6937315.57
      1659838.20      6937504.09
#Sta/Elev= 30
  3807.5 1757.60  3823.0 1756.81  3829.0 1757.88  3838.1 1757.19  3880.2 1757.44
  4003.5 1755.65  4117.8 1755.58  4126.9 1755.11  4147.9 1755.50  4220.1 1754.35
  4298.3 1754.03  4464.0 1754.30  4566.1 1753.84  4710.1 1754.33  4814.2 1753.82
  4876.1 1753.37  4916.2 1753.88  4948.7 1753.12  4970.5 1751.44  5005.0 1746.92
  5005.5 1746.42  5023.5 1746.42  5024.0 1746.92  5043.0 1748.69  5049.7 1750.03
  5056.2 1752.26  5070.5 1755.90  5092.5 1757.83  5131.8 1759.35  5247.8 1762.86
#Mann=7,-1,0
  3807.5   0.035       0  4710.1    0.07       0  4814.2   0.035       0
  4876.1    0.07       0  5005.0    0.07       0  5024.0    0.07       0
  5131.8   0.035       0
Bank Sta=5005,5024
Exp/Cntr=0.3,0.1

Type RM Length L Ch R = 1,9132,336,336,336
BEGIN DESCRIPTION:
Mapping XS 03c0692c
END DESCRIPTION:
XS GIS Cut Line= 5
      1659045.08      6936249.32      1659539.88      6937014.97
      1659443.20      6937257.95      1659441.19      6937375.98
      1659437.72      6937690.58
#Sta/Elev= 30
  3710.9 1756.60  3929.9 1755.51  3952.4 1755.53  4078.4 1755.28  4101.6 1754.78
  4107.5 1755.19  4216.4 1753.91  4245.1 1754.33  4267.8 1753.79  4527.8 1753.53
  4542.8 1753.73  4554.8 1756.26  4564.1 1755.91  4570.0 1754.42  4578.5 1753.88
  4609.2 1753.84  4729.2 1753.89  4881.4 1752.35  4933.5 1752.75  4964.1 1751.48
  4994.1 1748.81  5024.5 1747.82  5025.0 1747.32  5043.1 1747.32  5043.6 1747.82
  5104.1 1749.63  5174.1 1753.89  5224.1 1755.50  5244.1 1755.55  5316.7 1758.73
#Mann=7,-1,0
  3710.9   0.035       0  3929.9    0.07       0  3952.4   0.035       0
  4609.2    0.07       0  4933.5   0.035       0  5024.5   0.035       0
  5043.6   0.035       0
Bank Sta=5024.5,5043.6
Exp/Cntr=0.3,0.1

Type RM Length L Ch R = 1,8796,58,58,58
BEGIN DESCRIPTION:
Mapping XS 5c9b9f98
END DESCRIPTION:
XS GIS Cut Line= 6
      1658974.05      6936229.22      1659250.10      6936819.52
      1659488.41      6937012.42      1659253.52      6937134.66
      1659022.82      6937302.32      1658891.34      6937978.54
#Sta/Elev= 30
  3781.2 1756.04  4003.6 1754.90  4222.5 1754.09  4316.2 1753.59  4417.4 1752.94
  4429.1 1751.37  4442.0 1751.77  4449.9 1753.32  4470.8 1753.50  4670.6 1752.44
  4677.0 1754.13  4697.8 1756.59  4705.7 1756.50  4712.2 1753.83  4755.1 1753.16
  4775.3 1750.27  4827.6 1747.80  4932.6 1746.27  4974.4 1744.84  4974.9 1744.34
  4993.5 1744.84  5020.5 1745.82  5035.2 1749.12  5077.4 1749.75  5106.3 1753.18
  5127.1 1753.91  5602.7 1755.20  5694.3 1754.94  5829.9 1756.44  5979.1 1760.90
#Mann=11,-1,0
  3781.2   0.035       0  4003.6    0.07       0  4222.5   0.035       0
  4316.2    0.07       0  4417.4   0.035       0  4755.1    0.07       0
  4932.6   0.035       0  4974.4   0.035       0  4993.5   0.035       0
  5602.7    0.07       0  5694.3   0.035       0
Bank Sta=4974.4,4993.5
Exp/Cntr=0.3,0.1