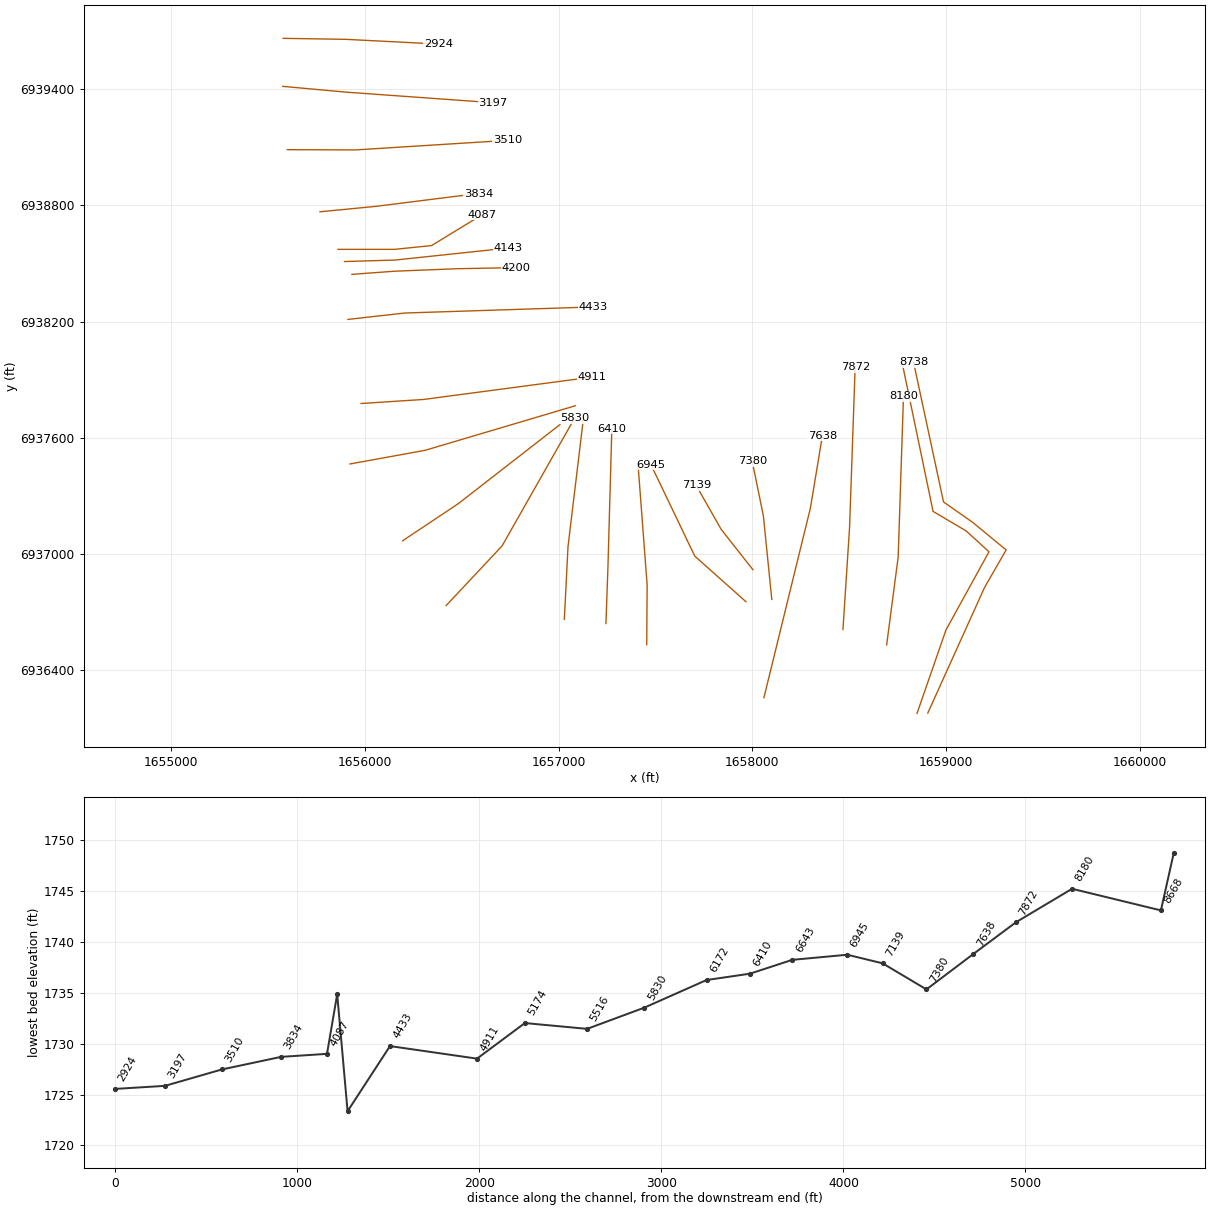
HEC-RAS study Chimney Creek 1097.prj: Chimney Creek 1097 Base Level Engineering

--- Chimney Creek 1097.g01 (geometry) --- (continued)

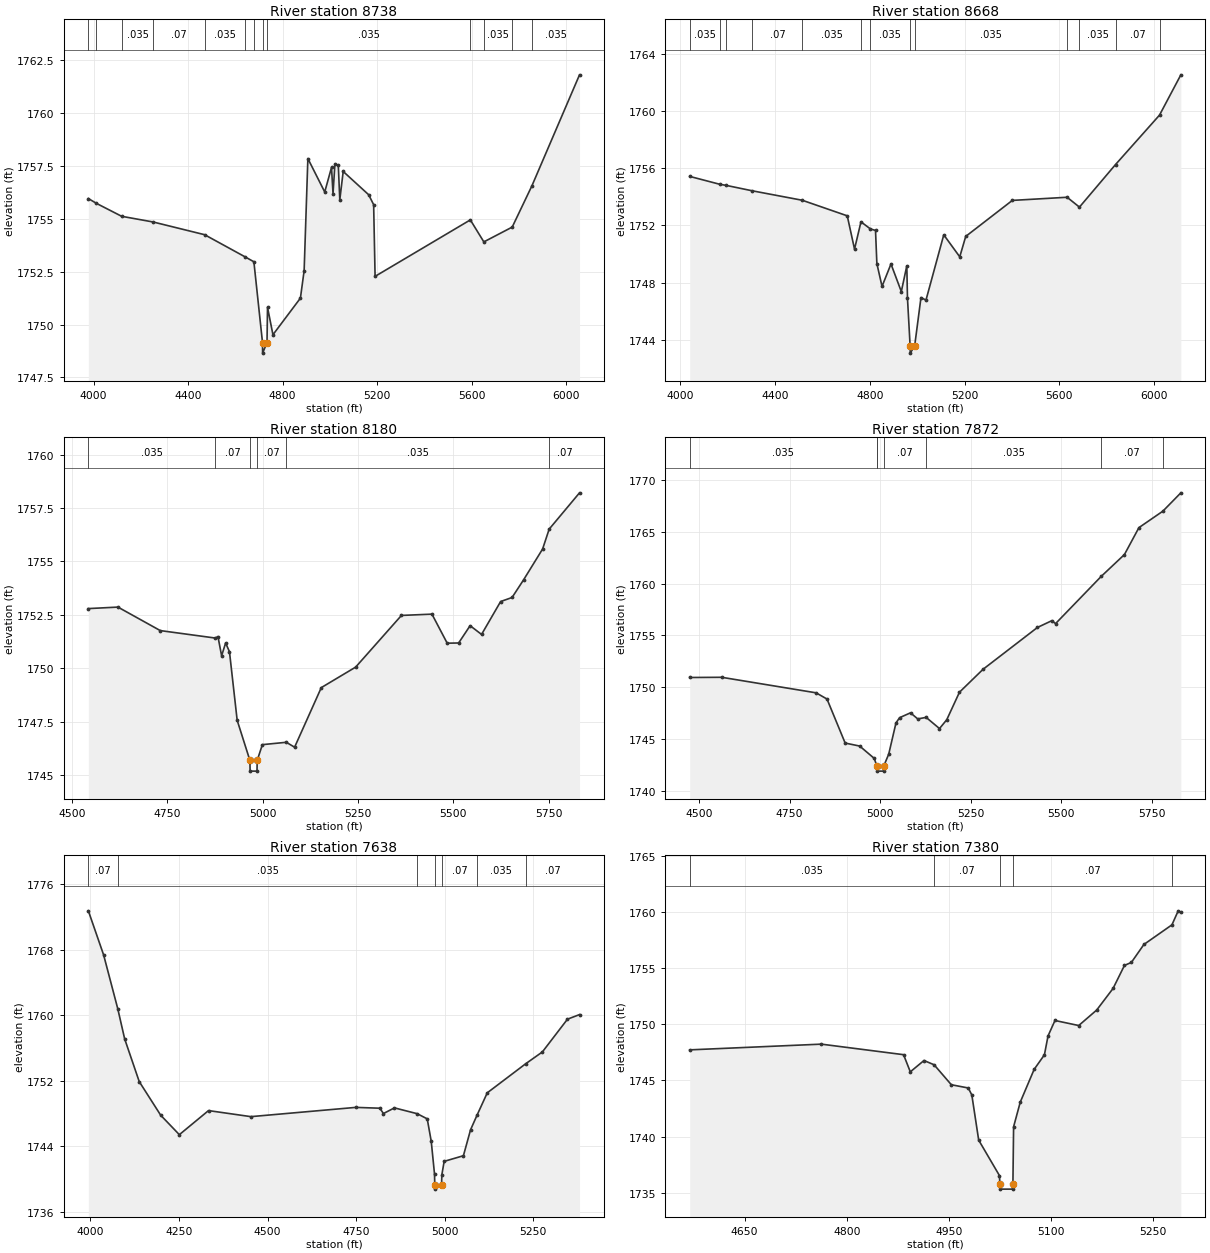
Type RM Length L Ch R = 1,8738,70,70,70
BEGIN DESCRIPTION:
Mapping XS 68a49bf7
END DESCRIPTION:
XS GIS Cut Line= 6
      1658906.35      6936178.90      1659199.39      6936827.34
      1659310.86      6937020.90      1659138.93      6937162.44
      1658987.41      6937268.75      1658832.77      6937989.30
#Sta/Elev= 30
  3977.5 1755.96  4012.0 1755.73  4118.6 1755.12  4252.4 1754.85  4469.8 1754.25
  4639.9 1753.21  4678.4 1752.97  4714.9 1749.15  4715.4 1748.65  4734.0 1749.15
  4736.1 1750.82  4759.1 1749.52  4875.4 1751.25  4891.2 1752.55  4907.0 1757.85
  4978.4 1756.27  5007.1 1757.43  5013.5 1756.19  5021.4 1757.57  5035.8 1757.53
  5042.2 1755.90  5056.6 1757.24  5164.4 1756.14  5185.5 1755.67  5191.6 1752.28
  5594.9 1754.95  5652.1 1753.91  5772.2 1754.61  5855.6 1756.56  6057.2 1761.81
#Mann=13,-1,0
  3977.5   0.035       0  4012.0    0.07       0  4118.6   0.035       0
  4252.4    0.07       0  4469.8   0.035       0  4639.9    0.07       0
  4678.4   0.035       0  4714.9   0.035       0  4734.0   0.035       0
  5594.9    0.07       0  5652.1   0.035       0  5772.2    0.07       0
  5855.6   0.035       0
Bank Sta=4714.9,4734
Exp/Cntr=0.3,0.1

Type RM Length L Ch R = 1,8668,488,488,488
BEGIN DESCRIPTION:
Mapping XS ebb87a25
END DESCRIPTION:
XS GIS Cut Line= 6
      1658850.78      6936177.12      1659000.10      6936607.71
      1659222.27      6937011.40      1659104.21      6937119.04
      1658933.51      6937219.90      1658772.29      6937994.45
#Sta/Elev= 30
  4039.8 1755.43  4166.5 1754.88  4194.3 1754.80  4304.5 1754.42  4515.1 1753.76
  4704.9 1752.67  4735.6 1750.34  4762.8 1752.25  4803.0 1751.75  4824.2 1751.65
  4829.9 1749.33  4851.7 1747.73  4889.5 1749.30  4933.1 1747.37  4956.3 1749.17
  4959.1 1746.91  4970.3 1743.56  4970.8 1743.06  4989.4 1743.56  5016.1 1746.95
  5037.2 1746.77  5112.3 1751.34  5179.8 1749.80  5205.0 1751.23  5401.7 1753.75
  5633.0 1753.97  5685.0 1753.28  5837.3 1756.26  6023.0 1759.72  6113.1 1762.54
#Mann=13,-1,0
  4039.8   0.035       0  4166.5    0.07       0  4194.3   0.035       0
  4304.5    0.07       0  4515.1   0.035       0  4762.8    0.07       0
  4803.0   0.035       0  4970.3   0.035       0  4989.4   0.035       0
  5633.0    0.07       0  5685.0   0.035       0  5837.3    0.07       0
  6023.0   0.035       0
Bank Sta=4970.3,4989.4
Exp/Cntr=0.3,0.1

Type RM Length L Ch R = 1,8180,308,308,308
BEGIN DESCRIPTION:
Mapping XS 66ff89db
END DESCRIPTION:
XS GIS Cut Line= 3
      1658693.87      6936531.03      1658753.40      6936984.14
      1658780.81      6937814.79
#Sta/Elev= 30
  4543.0 1752.79  4620.6 1752.86  4731.6 1751.76  4876.2 1751.41  4882.9 1751.48
  4892.5 1750.58  4903.0 1751.18  4913.1 1750.77  4933.3 1747.56  4966.7 1745.68
  4967.2 1745.18  4985.3 1745.18  4985.8 1745.68  4999.4 1746.42  5062.2 1746.53
  5083.9 1746.30  5153.9 1749.09  5244.0 1750.05  5364.1 1752.47  5444.1 1752.53
  5484.1 1751.17  5514.1 1751.18  5544.2 1751.99  5574.2 1751.58  5624.2 1753.12
  5654.2 1753.31  5684.2 1754.13  5734.3 1755.58  5751.5 1756.51  5831.1 1758.21
#Mann=6,-1,0
  4543.0   0.035       0  4876.2    0.07       0  4966.7    0.07       0
  4985.8    0.07       0  5062.2   0.035       0  5751.5    0.07       0
Bank Sta=4966.7,4985.8
Exp/Cntr=0.3,0.1

Type RM Length L Ch R = 1,7872,234,234,234
BEGIN DESCRIPTION:
Mapping XS 4b0ff767
END DESCRIPTION:
XS GIS Cut Line= 3
      1658468.37      6936609.90      1658502.45      6937136.73
      1658531.29      6937963.60
#Sta/Elev= 30
  4474.4 1750.94  4562.7 1750.96  4823.2 1749.46  4853.3 1748.86  4903.4 1744.61
  4943.5 1744.32  4983.6 1743.13  4990.1 1742.48  4990.9 1742.40  4991.4 1741.90
  5009.5 1741.90  5010.0 1742.40  5023.6 1743.54  5043.6 1746.55  5053.6 1747.06
  5083.7 1747.53  5103.7 1746.94  5126.8 1747.09  5163.7 1746.01  5183.7 1746.86
  5218.8 1749.52  5283.8 1751.73  5433.9 1755.77  5473.9 1756.43  5483.9 1756.14
  5609.9 1760.70  5674.0 1762.81  5714.0 1765.41  5780.1 1767.00  5829.7 1768.77
#Mann=7,-1,0
  4474.4   0.035       0  4990.1    0.07       0  4990.9    0.07       0
  5010.0    0.07       0  5126.8   0.035       0  5609.9    0.07       0
  5780.1   0.035       0
Bank Sta=4990.9,5010
Exp/Cntr=0.3,0.1

Type RM Length L Ch R = 1,7638,258,258,258
BEGIN DESCRIPTION:
Mapping XS 3ae42e42
END DESCRIPTION:
XS GIS Cut Line= 3
      1658060.39      6936258.40      1658300.20      6937236.56
      1658362.39      6937611.51
#Sta/Elev= 30
  3994.0 1772.77  4037.1 1767.39  4077.0 1760.83  4096.5 1757.14  4137.7 1751.92
  4198.4 1747.81  4251.0 1745.44  4333.4 1748.38  4453.0 1747.64  4749.3 1748.77
  4817.3 1748.67  4827.4 1748.02  4858.5 1748.71  4922.8 1748.00  4951.1 1747.37
  4962.4 1744.64  4971.7 1740.62  4972.4 1739.29  4972.9 1738.79  4991.6 1739.29
  4992.3 1740.52  4998.9 1742.18  5053.3 1742.87  5073.5 1746.04  5091.9 1747.83
  5120.7 1750.55  5228.9 1754.09  5276.3 1755.54  5347.2 1759.54  5381.2 1760.10
#Mann=7,-1,0
  3994.0    0.07       0  4077.0   0.035       0  4922.8    0.07       0
  4972.4    0.07       0  4991.6    0.07       0  5091.9   0.035       0
  5228.9    0.07       0
Bank Sta=4972.4,4991.6
Exp/Cntr=0.3,0.1

Type RM Length L Ch R = 1,7380,241,241,241
BEGIN DESCRIPTION:
Mapping XS 139d135f
END DESCRIPTION:
XS GIS Cut Line= 3
      1658100.96      6936765.45      1658057.57      6937196.80
      1657999.71      6937479.20
#Sta/Elev= 30
  4569.2 1747.73  4762.7 1748.24  4883.5 1747.30  4893.4 1745.77  4913.5 1746.78
  4928.4 1746.40  4953.7 1744.62  4978.6 1744.33  4983.8 1743.71  4993.9 1739.68
  5024.4 1736.52  5025.0 1735.81  5025.5 1735.31  5043.7 1735.31  5044.2 1735.81
  5045.2 1740.87  5055.0 1743.07  5075.4 1745.99  5090.5 1747.29  5095.8 1748.97
  5106.0 1750.35  5140.9 1749.90  5167.3 1751.28  5191.4 1753.21  5208.1 1755.26
  5218.3 1755.53  5236.7 1757.13  5277.9 1758.88  5287.1 1760.13  5291.0 1760.01
#Mann=5,-1,0
  4569.2   0.035       0  4928.4    0.07       0  5025.0    0.07       0
  5044.2    0.07       0  5277.9   0.035       0
Bank Sta=5025,5044.2
Exp/Cntr=0.3,0.1

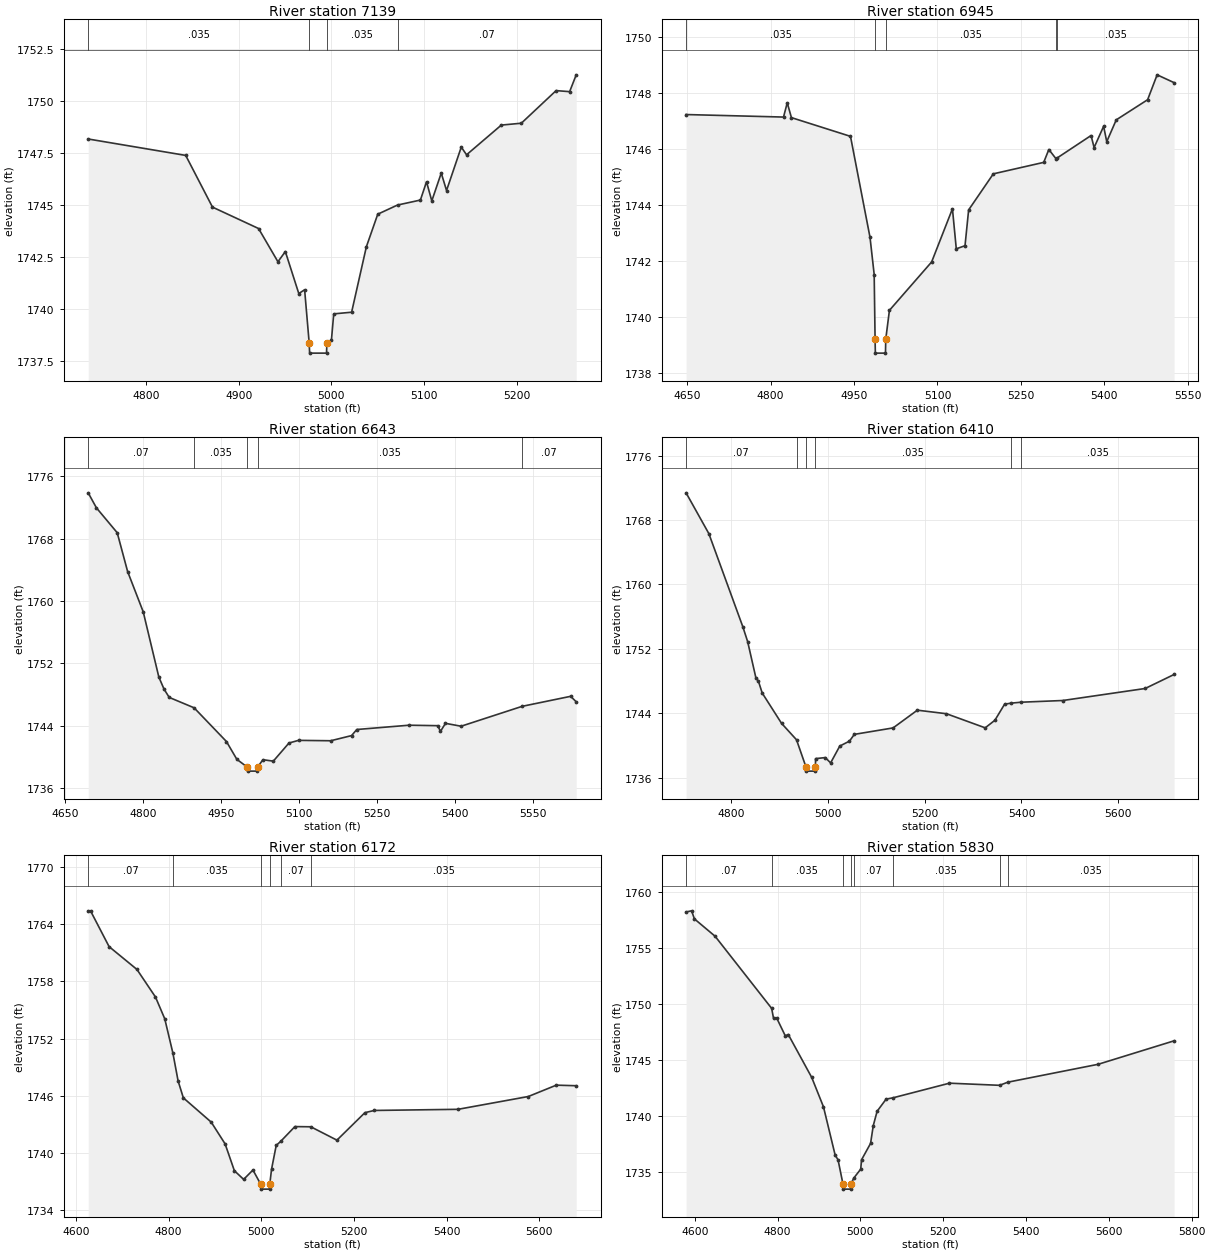
Type RM Length L Ch R = 1,7139,194,194,194
BEGIN DESCRIPTION:
Mapping XS 25a8b363
END DESCRIPTION:
XS GIS Cut Line= 3
      1658003.78      6936918.61      1657839.74      6937126.92
      1657710.62      6937354.16
#Sta/Elev= 30
  4737.7 1748.18  4842.9 1747.39  4871.8 1744.90  4921.5 1743.87  4942.4 1742.27
  4950.4 1742.76  4964.9 1740.74  4971.2 1740.92  4976.1 1738.37  4976.6 1737.87
  4994.8 1737.87  4995.3 1738.37  5000.1 1738.49  5002.6 1739.76  5021.9 1739.84
  5037.8 1742.99  5050.1 1744.56  5071.4 1745.00  5096.1 1745.24  5102.7 1746.12
  5108.4 1745.20  5118.6 1746.54  5124.3 1745.70  5140.2 1747.79  5145.9 1747.42
  5183.4 1748.85  5205.0 1748.94  5242.5 1750.51  5257.1 1750.46  5264.2 1751.27
#Mann=4,-1,0
  4737.7   0.035       0  4976.1   0.035       0  4995.3   0.035       0
  5071.4    0.07       0
Bank Sta=4976.1,4995.3
Exp/Cntr=0.3,0.1

Type RM Length L Ch R = 1,6945,302,302,302
BEGIN DESCRIPTION:
Mapping XS cd648e2e
END DESCRIPTION:
XS GIS Cut Line= 3
      1657967.58      6936753.56      1657703.45      6936988.90
      1657477.09      6937461.09
#Sta/Elev= 30
  4648.0 1747.24  4823.2 1747.15  4829.9 1747.66  4837.4 1747.13  4943.6 1746.46
  4978.7 1742.85  4986.2 1741.52  4987.8 1739.21  4988.3 1738.71  5006.5 1738.71
  5007.0 1739.21  5013.6 1740.24  5089.5 1741.97  5126.9 1743.87  5133.8 1742.44
  5149.5 1742.55  5156.0 1743.83  5200.4 1745.12  5291.0 1745.53  5300.2 1745.99
  5313.5 1745.65  5314.6 1745.68  5376.1 1746.49  5381.6 1746.06  5398.7 1746.82
  5404.3 1746.27  5421.4 1747.05  5477.8 1747.77  5494.9 1748.66  5525.4 1748.38
#Mann=5,-1,0
  4648.0   0.035       0  4987.8   0.035       0  5007.0   0.035       0
  5313.5    0.07       0  5314.6   0.035       0
Bank Sta=4987.8,5007
Exp/Cntr=0.3,0.1

Type RM Length L Ch R = 1,6643,233,233,233
BEGIN DESCRIPTION:
Mapping XS 0705908c
END DESCRIPTION:
XS GIS Cut Line= 3
      1657455.41      6936532.23      1657457.50      6936840.70
      1657409.92      6937468.62
#Sta/Elev= 30
  4695.0 1773.85  4710.8 1771.93  4750.8 1768.74  4770.8 1763.77  4800.8 1758.61
  4830.8 1750.26  4840.8 1748.71  4850.8 1747.65  4898.6 1746.32  4960.8 1742.00
  4980.8 1739.72  5001.1 1738.71  5001.6 1738.21  5020.0 1738.21  5020.5 1738.71
  5030.9 1739.67  5050.9 1739.49  5081.0 1741.81  5099.4 1742.15  5161.2 1742.10
  5201.3 1742.76  5211.4 1743.54  5311.7 1744.09  5367.1 1744.03  5372.2 1743.30
  5381.9 1744.33  5411.9 1743.96  5529.4 1746.51  5622.5 1747.79  5633.2 1747.09
#Mann=5,-1,0
  4695.0    0.07       0  4898.6   0.035       0  5001.1   0.035       0
  5020.5   0.035       0  5529.4    0.07       0
Bank Sta=5001.1,5020.5
Exp/Cntr=0.3,0.1

Type RM Length L Ch R = 1,6410,238,238,238
BEGIN DESCRIPTION:
Mapping XS a3fb078b
END DESCRIPTION:
XS GIS Cut Line= 3
      1657244.83      6936641.00      1657255.24      6936935.31
      1657275.29      6937647.63
#Sta/Elev= 30
  4707.9 1771.37  4754.9 1766.31  4825.0 1754.76  4835.0 1752.91  4852.1 1748.39
  4857.1 1748.02  4865.0 1746.54  4905.0 1742.77  4935.8 1740.74  4955.4 1737.35
  4955.9 1736.85  4974.3 1736.85  4974.8 1737.35  4975.1 1738.40  4995.1 1738.53
  5006.2 1737.87  5025.1 1739.96  5045.1 1740.57  5055.1 1741.41  5135.1 1742.21
  5185.2 1744.41  5245.2 1743.97  5325.2 1742.22  5345.2 1743.16  5365.2 1745.15
  5378.2 1745.28  5399.7 1745.40  5485.3 1745.61  5655.3 1747.10  5715.0 1748.84
#Mann=6,-1,0
  4707.9    0.07       0  4935.8   0.035       0  4955.4   0.035       0
  4974.8   0.035       0  5378.2    0.07       0  5399.7   0.035       0
Bank Sta=4955.4,4974.8
Exp/Cntr=0.3,0.1

Type RM Length L Ch R = 1,6172,342,342,342
BEGIN DESCRIPTION:
Mapping XS a273a1b8
END DESCRIPTION:
XS GIS Cut Line= 3
      1657030.00      6936662.98      1657048.98      6937037.61
      1657129.90      6937710.66
#Sta/Elev= 30
  4626.7 1765.38  4631.7 1765.38  4671.8 1761.63  4731.9 1759.24  4771.9 1756.35
  4791.9 1754.07  4809.5 1750.47  4820.7 1747.56  4832.0 1745.79  4892.1 1743.25
  4922.1 1740.97  4942.1 1738.16  4962.1 1737.25  4982.2 1738.23  4999.1 1736.73
  4999.6 1736.23  5018.0 1736.23  5018.5 1736.73  5022.3 1738.31  5032.4 1740.81
  5041.8 1741.22  5072.7 1742.78  5107.0 1742.76  5163.4 1741.36  5223.8 1744.24
  5243.9 1744.47  5424.7 1744.59  5576.3 1745.93  5636.7 1747.12  5679.7 1747.06
#Mann=6,-1,0
  4626.7    0.07       0  4809.5   0.035       0  4999.1   0.035       0
  5018.5   0.035       0  5041.8    0.07       0  5107.0   0.035       0
Bank Sta=4999.1,5018.5
Exp/Cntr=0.3,0.1

Type RM Length L Ch R = 1,5830,314,314,314
BEGIN DESCRIPTION:
Mapping XS 1a29a754
END DESCRIPTION:
XS GIS Cut Line= 3
      1656420.23      6936734.02      1656708.65      6937041.63
      1657082.14      6937699.76
#Sta/Elev= 30
  4579.2 1758.19  4592.5 1758.29  4599.4 1757.57  4649.2 1756.03  4785.8 1749.61
  4790.3 1748.74  4797.7 1748.77  4818.7 1747.17  4826.0 1747.28  4882.6 1743.46
  4911.0 1740.84  4939.3 1736.53  4946.1 1736.14  4957.8 1734.02  4958.3 1733.52
  4977.0 1733.52  4977.5 1734.02  4984.7 1734.53  5000.9 1735.30  5003.0 1736.14
  5024.7 1737.59  5031.2 1739.17  5040.5 1740.45  5062.2 1741.53  5079.1 1741.65
  5215.2 1742.95  5336.1 1742.76  5356.3 1743.04  5574.1 1744.63  5757.6 1746.72
#Mann=8,-1,0
  4579.2    0.07       0  4785.8   0.035       0  4957.8    0.07       0
  4977.5   0.035       0  4984.7    0.07       0  5079.1   0.035       0
  5336.1    0.07       0  5356.3   0.035       0
Bank Sta=4957.8,4977.5
Exp/Cntr=0.3,0.1

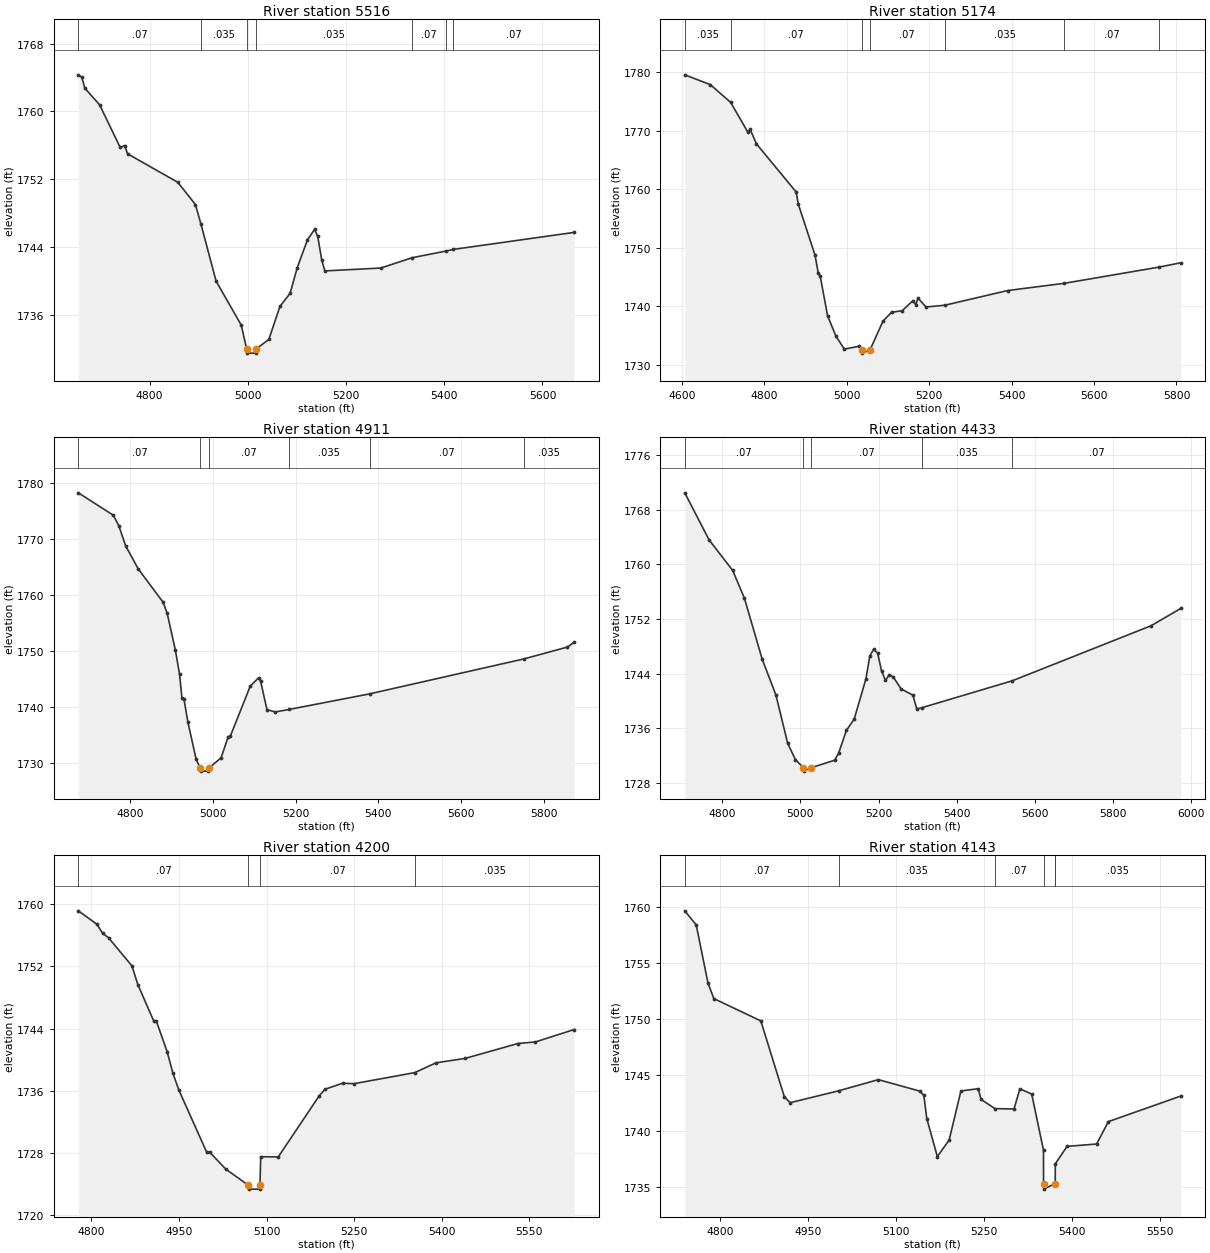
Type RM Length L Ch R = 1,5516,342,342,342
BEGIN DESCRIPTION:
Mapping XS 4a8aaca8
END DESCRIPTION:
XS GIS Cut Line= 3
      1656195.32      6937068.16      1656482.80      6937259.81
      1657007.18      6937667.63
#Sta/Elev= 30
  4654.7 1764.31  4661.9 1764.02  4667.9 1762.73  4697.9 1760.78  4740.0 1755.73
  4749.0 1755.96  4755.0 1754.98  4857.2 1751.62  4893.2 1748.99  4904.5 1746.66
  4935.3 1739.94  4986.4 1734.76  4997.5 1731.94  4998.0 1731.44  5016.7 1731.44
  5017.2 1731.94  5042.7 1733.06  5065.3 1736.96  5086.1 1738.51  5100.6 1741.55
  5121.4 1744.83  5135.9 1746.06  5142.3 1745.22  5150.3 1742.47  5156.7 1741.15
  5270.7 1741.49  5334.6 1742.71  5404.1 1743.50  5418.3 1743.69  5664.5 1745.70
#Mann=7,-1,0
  4654.7    0.07       0  4904.5   0.035       0  4997.5   0.035       0
  5017.2   0.035       0  5334.6    0.07       0  5404.1   0.035       0
  5418.3    0.07       0
Bank Sta=4997.5,5017.2
Exp/Cntr=0.3,0.1

Type RM Length L Ch R = 1,5174,263,263,263
BEGIN DESCRIPTION:
Mapping XS 797092aa
END DESCRIPTION:
XS GIS Cut Line= 3
      1655924.04      6937464.75      1656311.23      6937535.07
      1657087.48      6937765.29
#Sta/Elev= 30
  4606.9 1779.55  4668.9 1777.87  4718.3 1774.84  4760.1 1769.73  4765.2 1770.29
  4780.7 1767.76  4877.1 1759.54  4882.3 1757.47  4923.0 1748.73  4930.5 1745.78
  4935.5 1745.16  4953.4 1738.38  4973.8 1734.90  4994.1 1732.69  5029.4 1733.18
  5036.2 1732.51  5036.7 1732.01  5056.0 1732.51  5087.8 1737.46  5108.7 1739.00
  5134.3 1739.25  5160.8 1740.99  5167.5 1740.27  5172.7 1741.42  5192.1 1739.89
  5237.6 1740.19  5390.3 1742.70  5528.1 1743.94  5756.5 1746.69  5810.1 1747.44
#Mann=7,-1,0
  4606.9   0.035       0  4718.3    0.07       0  5036.2    0.07       0
  5056.0    0.07       0  5237.6   0.035       0  5528.1    0.07       0
  5756.5   0.035       0
Bank Sta=5036.2,5056
Exp/Cntr=0.3,0.1

Type RM Length L Ch R = 1,4911,478,478,478
BEGIN DESCRIPTION:
Mapping XS 402100f9
END DESCRIPTION:
XS GIS Cut Line= 3
      1655980.83      6937776.82      1656303.78      6937797.66
      1657171.06      6937912.73
#Sta/Elev= 30
  4675.0 1778.27  4759.3 1774.28  4772.7 1772.41  4789.4 1768.79  4819.5 1764.70
  4879.6 1758.74  4889.6 1756.78  4909.7 1750.11  4919.7 1745.83  4925.5 1741.56
  4930.5 1741.33  4939.7 1737.33  4959.8 1730.63  4969.9 1729.02  4970.4 1728.52
  4989.2 1728.52  4989.7 1729.02  5020.0 1730.89  5037.2 1734.65  5042.2 1734.73
  5090.6 1743.72  5110.5 1745.19  5115.6 1744.59  5131.0 1739.51  5151.2 1739.10
  5184.6 1739.55  5379.0 1742.33  5752.1 1748.58  5857.3 1750.70  5873.5 1751.55
#Mann=6,-1,0
  4675.0    0.07       0  4969.9    0.07       0  4989.7    0.07       0
  5184.6   0.035       0  5379.0    0.07       0  5752.1   0.035       0
Bank Sta=4969.9,4989.7
Exp/Cntr=0.3,0.1

Type RM Length L Ch R = 1,4433,233,233,233
BEGIN DESCRIPTION:
Mapping XS 75c8176d
END DESCRIPTION:
XS GIS Cut Line= 3
      1655913.15      6938210.85      1656206.56      6938243.84
      1657180.39      6938275.27
#Sta/Elev= 30
  4704.0 1770.49  4766.2 1763.60  4826.6 1759.13  4856.8 1755.04  4902.2 1746.13
  4937.3 1740.90  4967.5 1733.81  4987.2 1731.44  5007.8 1730.25  5008.3 1729.75
  5027.6 1730.25  5087.7 1731.35  5097.8 1732.37  5117.8 1735.71  5137.8 1737.38
  5167.8 1743.26  5177.8 1746.65  5187.8 1747.58  5197.8 1747.02  5207.8 1744.41
  5217.8 1743.04  5227.8 1743.88  5237.8 1743.53  5257.8 1741.79  5288.1 1740.87
  5297.9 1738.86  5312.0 1739.05  5542.3 1742.97  5898.2 1751.04  5973.6 1753.56
#Mann=5,-1,0
  4704.0    0.07       0  5007.8    0.07       0  5027.6    0.07       0
  5312.0   0.035       0  5542.3    0.07       0
Bank Sta=5007.8,5027.6
Exp/Cntr=0.3,0.1

Type RM Length L Ch R = 1,4200,57,57,57
BEGIN DESCRIPTION:
Mapping XS a8fb9224
END DESCRIPTION:
XS GIS Cut Line= 4
      1655933.40      6938443.43      1656154.76      6938459.70
      1656481.37      6938472.72      1656781.49      6938478.12
#Sta/Elev= 30
  4777.8 1759.14  4809.5 1757.42  4819.5 1756.24  4829.5 1755.68  4869.6 1752.06
  4879.7 1749.66  4906.6 1745.03  4911.6 1744.92  4929.8 1741.05  4939.8 1738.25
  4949.9 1736.10  4997.4 1728.14  5002.4 1728.14  5030.0 1725.95  5068.9 1723.86
  5069.4 1723.36  5088.3 1723.36  5088.8 1723.86  5090.1 1727.53  5120.1 1727.50
  5190.2 1735.35  5200.2 1736.20  5230.2 1736.97  5250.2 1736.92  5353.8 1738.34
  5390.3 1739.60  5440.3 1740.17  5530.3 1742.08  5560.3 1742.28  5626.8 1743.88
#Mann=4,-1,0
  4777.8    0.07       0  5068.9    0.07       0  5088.8    0.07       0
  5353.8   0.035       0
Bank Sta=5068.9,5088.8
Exp/Cntr=0.3,0.1

Type RM Length L Ch R = 1,4143,56,56,56
BEGIN DESCRIPTION:
Mapping XS a462970a
END DESCRIPTION:
XS GIS Cut Line= 3
      1655895.47      6938509.62      1656155.85      6938517.21
      1656737.48      6938579.06
#Sta/Elev= 30
  4740.3 1759.70  4759.8 1758.44  4779.8 1753.26  4789.8 1751.86  4869.9 1749.87
  4909.9 1743.11  4919.9 1742.56  5003.1 1743.63  5070.3 1744.62  5140.7 1743.60
  5147.9 1743.21  5152.9 1741.14  5170.9 1737.75  5191.0 1739.22  5211.1 1743.61
  5240.5 1743.81  5245.5 1742.85  5269.3 1742.03  5301.6 1742.00  5311.7 1743.80
  5331.8 1743.33  5351.9 1738.31  5352.0 1735.34  5352.5 1734.84  5371.9 1735.34
  5372.0 1737.10  5392.1 1738.66  5442.4 1738.87  5462.5 1740.87  5585.7 1743.15
#Mann=6,-1,0
  4740.3    0.07       0  5003.1   0.035       0  5269.3    0.07       0
  5352.0    0.07       0  5371.9    0.07       0  5372.0   0.035       0
Bank Sta=5352,5371.9
Exp/Cntr=0.3,0.1

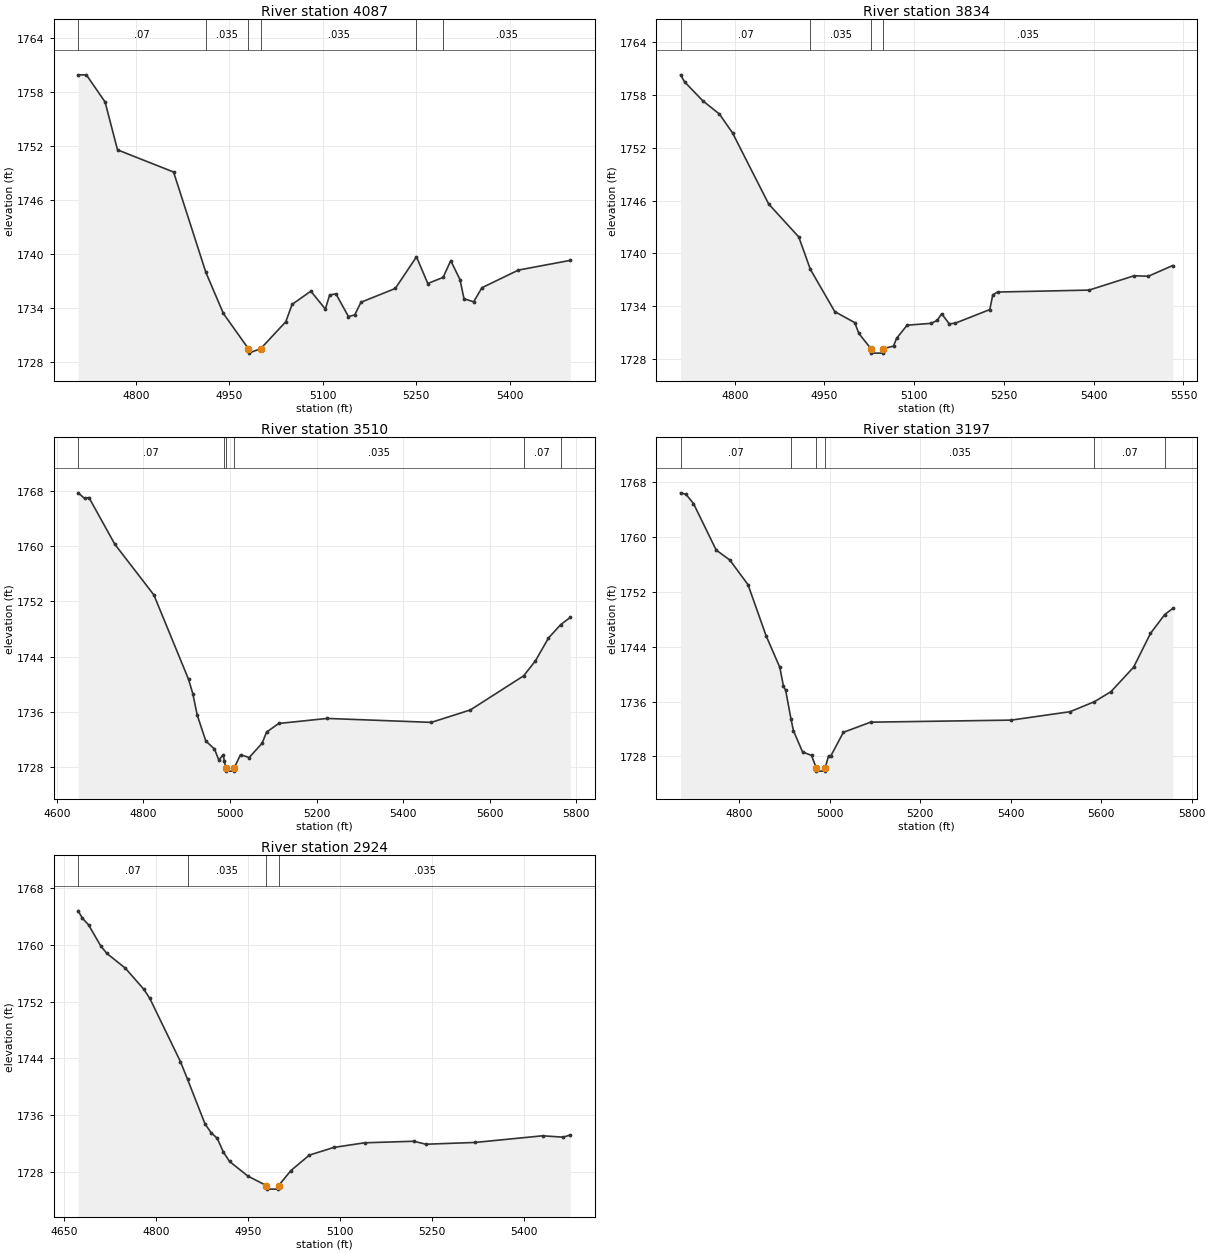
Type RM Length L Ch R = 1,4087,253,253,253
BEGIN DESCRIPTION:
Mapping XS 1f700f4b
END DESCRIPTION:
XS GIS Cut Line= 4
      1655861.78      6938572.55      1656154.76      6938572.55
      1656344.65      6938592.08      1656606.17      6938751.60
#Sta/Elev= 30
  4707.3 1759.88  4720.5 1759.89  4750.5 1756.88  4770.5 1751.56  4860.5 1749.10
  4912.4 1737.95  4940.5 1733.39  4980.6 1729.49  4981.1 1728.99  5000.5 1729.49
  5040.7 1732.48  5050.8 1734.40  5080.9 1735.87  5104.2 1733.88  5111.1 1735.45
  5121.2 1735.57  5141.3 1733.05  5151.3 1733.23  5161.4 1734.64  5216.5 1736.17
  5250.5 1739.68  5268.7 1736.72  5293.3 1737.40  5305.5 1739.26  5320.4 1737.15
  5326.8 1735.03  5342.3 1734.69  5355.6 1736.25  5414.1 1738.21  5497.5 1739.29
#Mann=6,-1,0
  4707.3    0.07       0  4912.4   0.035       0  4980.6   0.035       0
  5000.5   0.035       0  5250.5    0.07       0  5293.3   0.035       0
Bank Sta=4980.6,5000.5
Exp/Cntr=0.3,0.1

Type RM Length L Ch R = 1,3834,324,324,324
BEGIN DESCRIPTION:
Mapping XS e80357ac
END DESCRIPTION:
XS GIS Cut Line= 3
      1655768.46      6938766.41      1656058.19      6938794.63
      1656585.56      6938860.82
#Sta/Elev= 30
  4709.5 1760.26  4716.1 1759.47  4746.2 1757.34  4774.4 1755.81  4796.4 1753.66
  4856.7 1745.61  4907.0 1741.87  4926.4 1738.20  4967.2 1733.40  5000.6 1732.15
  5007.5 1730.92  5027.7 1729.19  5028.2 1728.69  5047.1 1728.69  5047.6 1729.19
  5065.4 1729.49  5070.4 1730.36  5088.1 1731.86  5128.4 1732.07  5138.5 1732.41
  5145.8 1733.16  5158.6 1732.01  5168.7 1732.09  5226.3 1733.63  5231.3 1735.30
  5239.3 1735.62  5392.2 1735.84  5467.7 1737.47  5491.2 1737.41  5532.1 1738.63
#Mann=4,-1,0
  4709.5    0.07       0  4926.4   0.035       0  5027.7   0.035       0
  5047.6   0.035       0
Bank Sta=5027.7,5047.6
Exp/Cntr=0.3,0.1

Type RM Length L Ch R = 1,3510,313,313,313
BEGIN DESCRIPTION:
Mapping XS 83db6961
END DESCRIPTION:
XS GIS Cut Line= 3
      1655600.07      6939087.10      1655951.68      6939085.79
      1656735.32      6939135.09
#Sta/Elev= 30
  4649.1 1767.70  4664.0 1766.89  4674.0 1767.02  4734.0 1760.25  4824.0 1752.94
  4904.0 1740.75  4914.0 1738.65  4924.0 1735.59  4944.0 1731.81  4964.0 1730.66
  4974.0 1729.06  4984.0 1729.83  4987.0 1728.88  4989.9 1727.96  4990.4 1727.46
  5009.3 1727.46  5009.8 1727.96  5024.1 1729.83  5044.1 1729.43  5074.2 1731.50
  5084.2 1733.10  5112.4 1734.35  5224.5 1735.08  5464.9 1734.51  5555.1 1736.31
  5678.1 1741.24  5705.4 1743.41  5735.5 1746.71  5763.9 1748.66  5785.9 1749.69
#Mann=6,-1,0
  4649.1    0.07       0  4987.0   0.035       0  4989.9   0.035       0
  5009.8   0.035       0  5678.1    0.07       0  5763.9   0.035       0
Bank Sta=4989.9,5009.8
Exp/Cntr=0.3,0.1

Type RM Length L Ch R = 1,3197,273,273,273
BEGIN DESCRIPTION:
Mapping XS 587fdb41
END DESCRIPTION:
XS GIS Cut Line= 3
      1655576.65      6939413.92      1655904.80      6939383.97
      1656661.23      6939329.62
#Sta/Elev= 30
  4670.3 1766.44  4682.1 1766.23  4698.8 1764.88  4749.0 1758.09  4779.1 1756.64
  4819.3 1753.05  4859.4 1745.58  4889.6 1740.99  4897.5 1738.30  4902.6 1737.62
  4914.4 1733.44  4919.7 1731.77  4939.8 1728.66  4959.8 1728.13  4970.0 1726.35
  4970.5 1725.85  4989.4 1725.85  4989.9 1726.35  4997.4 1728.07  5002.4 1728.07
  5030.1 1731.51  5090.2 1732.99  5401.0 1733.29  5531.4 1734.52  5585.1 1735.98
  5621.6 1737.44  5671.7 1741.01  5709.0 1745.94  5740.5 1748.69  5758.2 1749.58
#Mann=6,-1,0
  4670.3    0.07       0  4914.4   0.035       0  4970.0   0.035       0
  4989.9   0.035       0  5585.1    0.07       0  5740.5   0.035       0
Bank Sta=4970,4989.9
Exp/Cntr=0.3,0.1

Type RM Length L Ch R = 1,2924,316,316,316
BEGIN DESCRIPTION:
Mapping XS 36d1d15e
END DESCRIPTION:
XS GIS Cut Line= 3
      1655578.11      6939661.84      1655902.81      6939656.63
      1656380.15      6939632.33
#Sta/Elev= 30
  4672.9 1764.84  4679.8 1763.80  4689.8 1762.87  4709.8 1759.88  4719.8 1758.82
  4749.8 1756.75  4779.8 1753.79  4789.8 1752.47  4839.8 1743.54  4851.4 1741.04
  4879.8 1734.76  4889.8 1733.51  4899.8 1732.72  4909.8 1730.78  4919.8 1729.46
  4949.8 1727.39  4979.9 1726.05  4980.4 1725.55  4999.3 1725.55  4999.8 1726.05
  5019.9 1728.17  5049.9 1730.35  5090.0 1731.44  5140.0 1732.09  5220.1 1732.31
  5240.1 1731.89  5320.3 1732.14  5430.4 1733.08  5463.9 1732.89  5475.6 1733.19
#Mann=4,-1,0
  4672.9    0.07       0  4851.4   0.035       0  4979.9   0.035       0
  4999.8   0.035       0
Bank Sta=4979.9,4999.8
Exp/Cntr=0.3,0.1