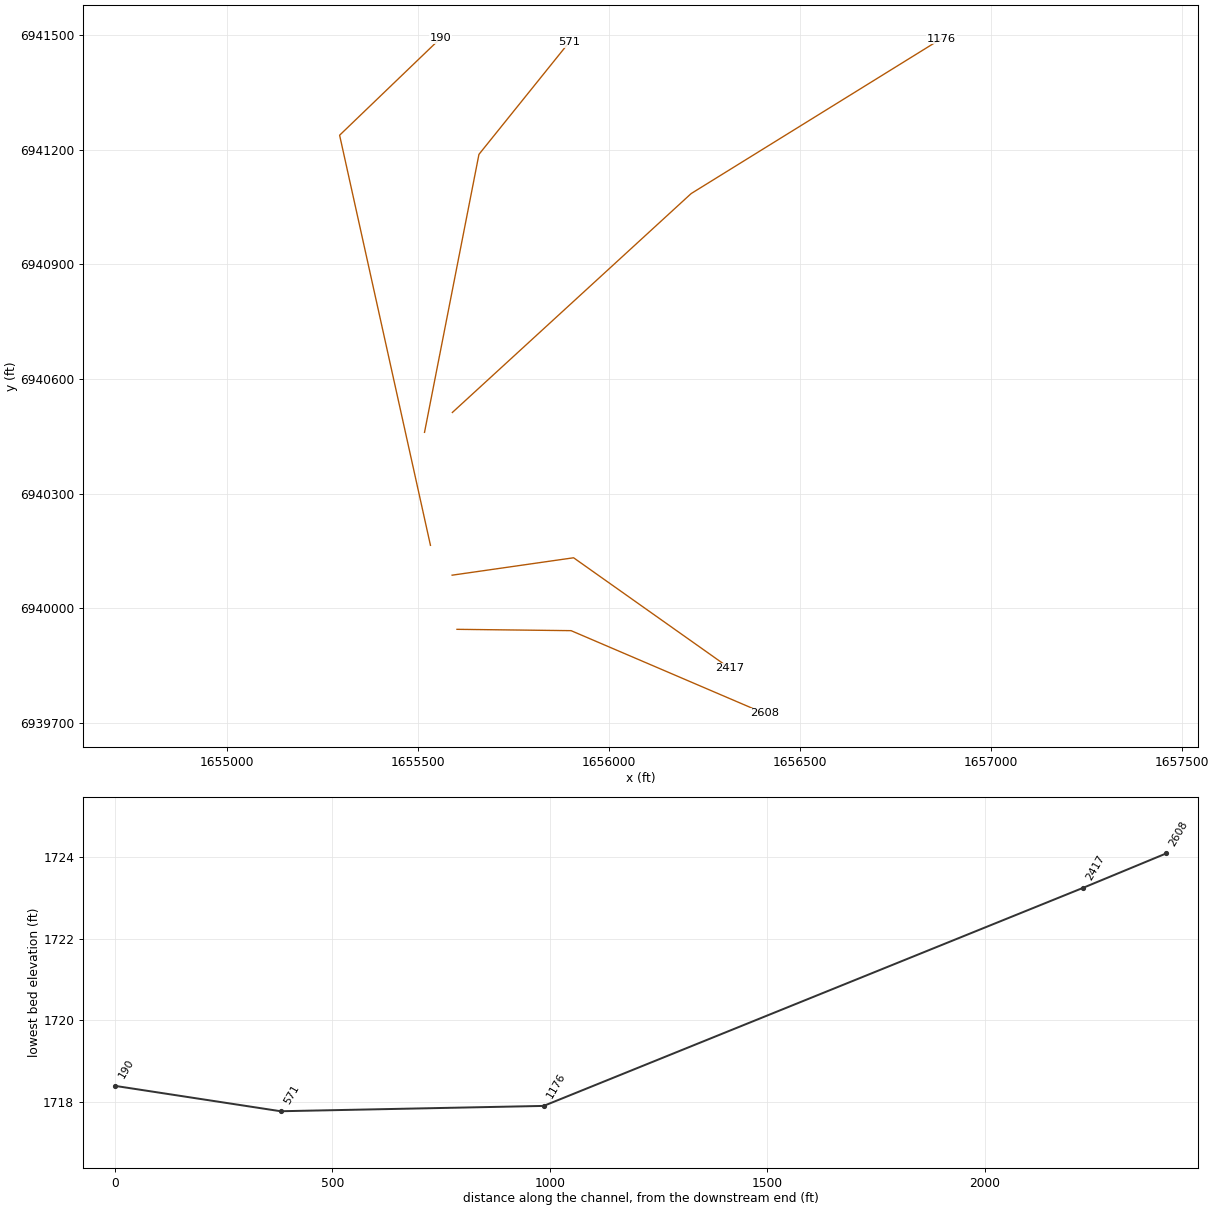
HEC-RAS study Chimney Creek 1097.prj: Chimney Creek 1097 Base Level Engineering

--- Chimney Creek 1097.g01 (geometry) --- (continued)

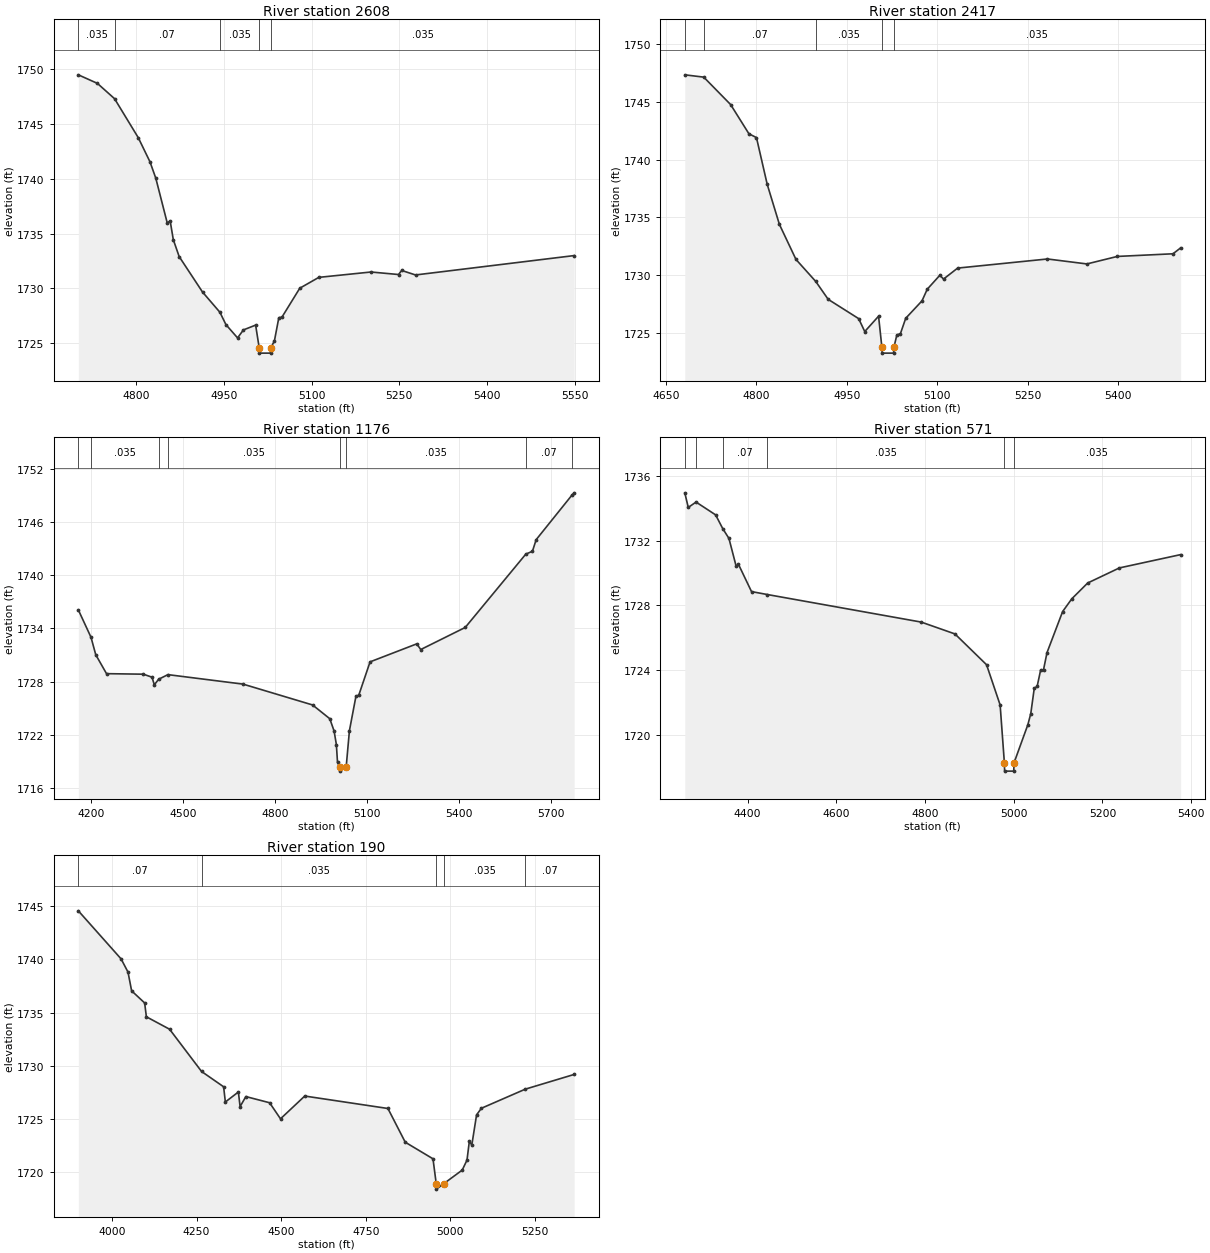
Type RM Length L Ch R = 1,2608,191,191,191
BEGIN DESCRIPTION:
Mapping XS 2d92bca8
END DESCRIPTION:
XS GIS Cut Line= 3
      1655602.42      6939944.82      1655901.07      6939941.35
      1656406.80      6939724.84
#Sta/Elev= 30
  4700.6 1749.50  4733.2 1748.72  4762.6 1747.32  4803.2 1743.76  4823.2 1741.56
  4833.2 1740.06  4852.8 1735.97  4857.8 1736.16  4863.2 1734.44  4873.2 1732.90
  4913.2 1729.66  4943.0 1727.81  4953.2 1726.69  4973.2 1725.47  4983.2 1726.20
  5004.1 1726.64  5010.2 1724.58  5010.7 1724.08  5029.6 1724.08  5030.1 1724.58
  5036.2 1725.18  5043.8 1727.31  5049.2 1727.37  5079.7 1730.01  5112.3 1731.00
  5201.6 1731.49  5248.7 1731.26  5254.2 1731.63  5277.8 1731.22  5549.4 1732.99
#Mann=5,-1,0
  4700.6   0.035       0  4762.6    0.07       0  4943.0   0.035       0
  5010.2   0.035       0  5030.1   0.035       0
Bank Sta=5010.2,5030.1
Exp/Cntr=0.3,0.1

Type RM Length L Ch R = 1,2417,1241,1241,1241
BEGIN DESCRIPTION:
Mapping XS 6fa36924
END DESCRIPTION:
XS GIS Cut Line= 3
      1655589.75      6940086.53      1655907.65      6940132.11
      1656316.46      6939842.93
#Sta/Elev= 30
  4681.5 1747.36  4712.9 1747.16  4757.5 1744.78  4787.8 1742.25  4800.3 1741.92
  4818.1 1737.87  4838.3 1734.40  4865.8 1731.36  4898.6 1729.45  4919.2 1727.90
  4969.7 1726.23  4979.8 1725.11  5002.7 1726.44  5008.2 1723.74  5008.7 1723.24
  5027.6 1723.24  5028.1 1723.74  5032.9 1724.79  5039.0 1724.94  5047.7 1726.26
  5074.7 1727.77  5083.4 1728.78  5104.3 1729.99  5110.4 1729.66  5133.8 1730.61
  5282.7 1731.40  5348.0 1730.97  5398.4 1731.62  5490.7 1731.85  5503.4 1732.36
#Mann=5,-1,0
  4681.5   0.035       0  4712.9    0.07       0  4898.6   0.035       0
  5008.2   0.035       0  5028.1   0.035       0
Bank Sta=5008.2,5028.1
Exp/Cntr=0.3,0.1

Type RM Length L Ch R = 1,1176,605,605,605
BEGIN DESCRIPTION:
Mapping XS 0ab9ee4e
END DESCRIPTION:
XS GIS Cut Line= 3
      1655590.41      6940512.43      1656215.42      6941085.35
      1656870.83      6941491.08
#Sta/Elev= 30
  4157.1 1736.09  4198.5 1733.00  4214.0 1731.03  4249.1 1728.90  4369.4 1728.84
  4397.7 1728.50  4405.1 1727.64  4419.3 1728.27  4449.6 1728.79  4694.9 1727.72
  4921.9 1725.37  4978.0 1723.82  4992.1 1722.43  4999.5 1720.91  5003.2 1718.91
  5010.0 1718.41  5010.5 1717.91  5031.6 1718.41  5042.1 1722.47  5063.3 1726.33
  5072.8 1726.49  5109.5 1730.23  5261.9 1732.26  5275.0 1731.62  5420.2 1734.11
  5618.0 1742.38  5639.6 1742.70  5651.8 1744.01  5768.3 1749.02  5775.8 1749.29
#Mann=8,-1,0
  4157.1    0.07       0  4198.5   0.035       0  4419.3    0.07       0
  4449.6   0.035       0  5010.0   0.035       0  5031.6   0.035       0
  5618.0    0.07       0  5768.3   0.035       0
Bank Sta=5010,5031.6
Exp/Cntr=0.3,0.1

Type RM Length L Ch R = 1,571,381,381,381
BEGIN DESCRIPTION:
Mapping XS a07e7e1d
END DESCRIPTION:
XS GIS Cut Line= 3
      1655517.50      6940460.36      1655659.97      6941187.94
      1655895.96      6941481.17
#Sta/Elev= 30
  4258.6 1734.94  4266.4 1734.04  4284.0 1734.37  4328.1 1733.58  4344.2 1732.73
  4358.1 1732.13  4374.5 1730.40  4379.6 1730.53  4409.0 1728.85  4444.5 1728.67
  4791.6 1726.97  4867.6 1726.24  4938.9 1724.34  4969.5 1721.86  4979.1 1718.28
  4979.6 1717.78  5000.2 1717.78  5000.7 1718.28  5032.1 1720.65  5038.6 1721.33
  5046.4 1722.88  5052.9 1723.00  5060.8 1724.01  5067.3 1724.03  5075.2 1725.09
  5110.4 1727.62  5131.2 1728.41  5166.9 1729.38  5238.4 1730.31  5376.4 1731.13
#Mann=6,-1,0
  4258.6    0.07       0  4284.0   0.035       0  4344.2    0.07       0
  4444.5   0.035       0  4979.1   0.035       0  5000.7   0.035       0
Bank Sta=4979.1,5000.7
Exp/Cntr=0.3,0.1

Type RM Length L Ch R = 1,190,0,0,0
BEGIN DESCRIPTION:
Chimney Creek 1097 2.0
END DESCRIPTION:
XS GIS Cut Line= 3
      1655533.05      6940164.64      1655295.28      6941238.02
      1655559.18      6941491.61
#Sta/Elev= 30
  3900.6 1744.56  4027.0 1740.04  4047.4 1738.80  4058.1 1737.04  4096.6 1735.90
  4101.7 1734.60  4170.3 1733.43  4264.8 1729.46  4330.0 1728.02  4335.1 1726.59
  4373.6 1727.53  4378.7 1726.16  4395.7 1727.10  4465.9 1726.52  4498.1 1725.01
  4569.8 1727.15  4815.6 1725.98  4866.8 1722.81  4948.8 1721.25  4958.4 1718.90
  4958.9 1718.40  4980.1 1718.90  5035.2 1720.19  5049.3 1721.13  5056.3 1722.92
  5063.5 1722.54  5077.6 1725.38  5091.8 1726.00  5221.8 1727.80  5366.0 1729.18
#Mann=5,-1,0
  3900.6    0.07       0  4264.8   0.035       0  4958.4   0.035       0
  4980.1   0.035       0  5221.8    0.07       0
Bank Sta=4958.4,4980.1
Exp/Cntr=0.3,0.1

Chan Stop Cuts=-1