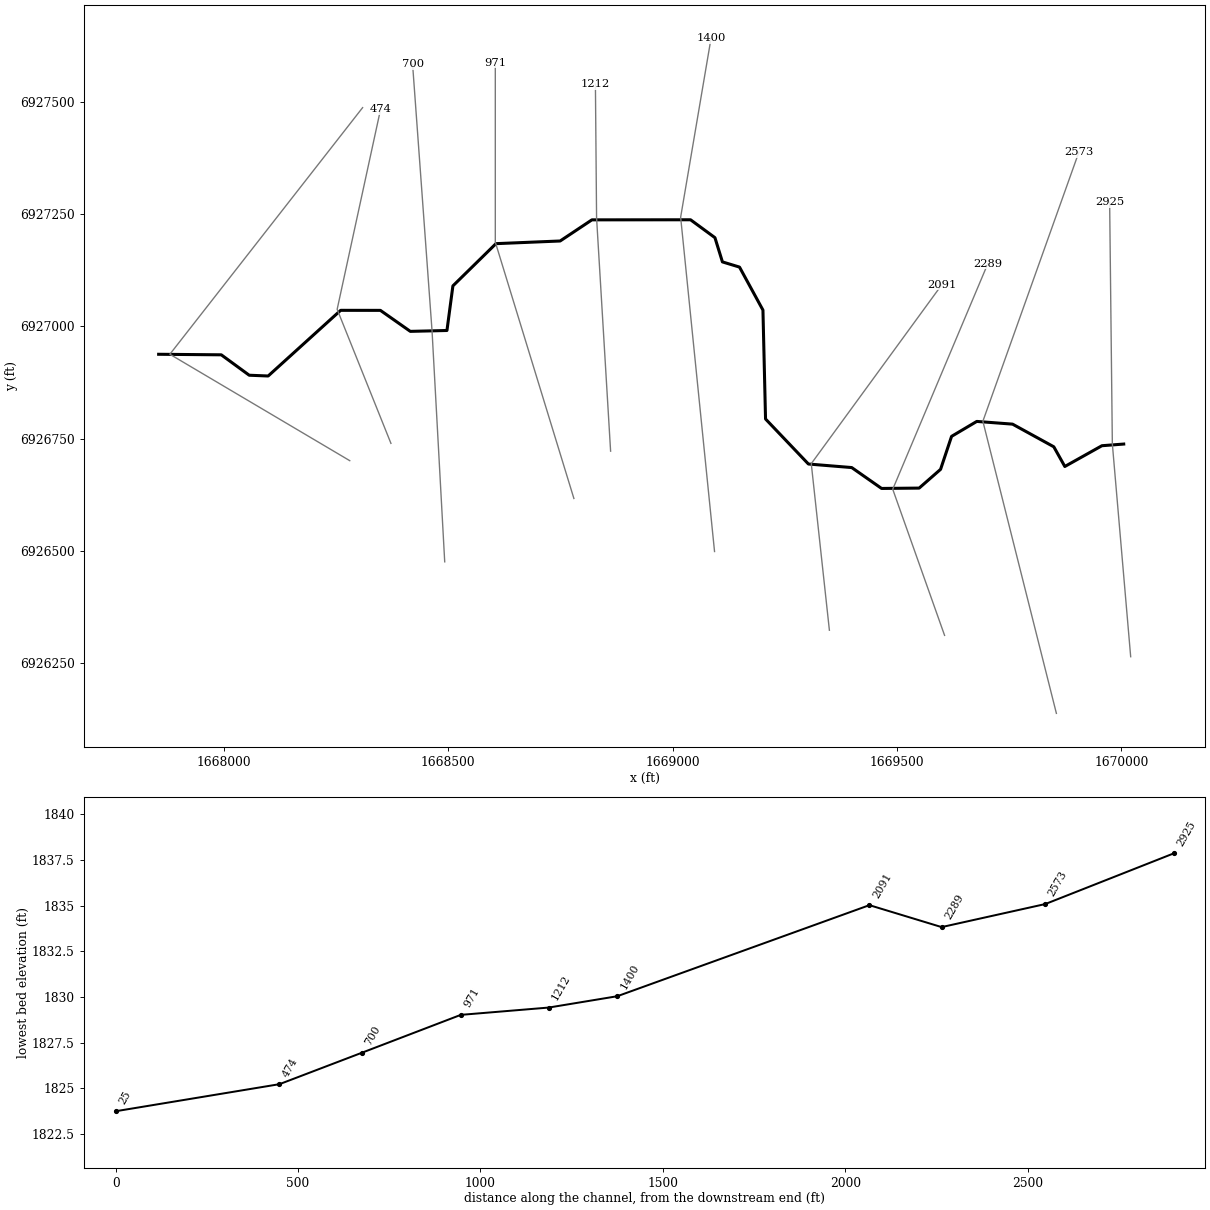
--- Chimney Creek 1098.prj (project) ---

Proj Title=Chimney Creek 1098 Base Level Engineering
Current Plan=p01
Default Exp/Contr=0.3,0.1
English Units
Geom File=g01
Flow File=f01
Plan File=p01
BEGIN DESCRIPTION:
Chimney Creek 1098
END DESCRIPTION:

--- Chimney Creek 1098.p01 (plan) ---

Plan Title=Multiple Run
Short Identifier=Multiple
Geom File=g01
Flow File=f01
Subcritical Flow
K Sum by GR= 0
Std Step Tol= 0.01
Critical Tol= 0.01
Num of Std Step Trials= 20
Max Error Tol= 0.3
Flow Tol Ratio= 0.001
Split Flow NTrial= 30
Split Flow Tol= 0.02
Split Flow Ratio= 0.02
Log Output Level= 0
Friction Slope Method= 1
Unsteady Friction Slope Method= 2
Unsteady Bridges Friction Slope Method= 1
Parabolic Critical Depth
Global Vel Dist=  1 , 1 , 1
Global Log Level= 0
CheckData=True
Encroach Param= -1, 0, 0, 0
BEGIN DESCRIPTION:
Multiple Run
END DESCRIPTION:

--- Chimney Creek 1098.f01 (steady flow) ---

Flow Title=Multiple
Number of Profiles=7
Profile Names=10-year,25-year,50-year,1pct_min,100-year,1pct_plu,500-year
River Rch & RM= Chimney Creek 10,Reach-1,2925
     249     346     425     261     521    1039     789
River Rch & RM= Chimney Creek 10,Reach-1,2289
     262     363     447     274     547    1091     829
Boundary for River Rch & Prof#=Chimney Creek 10,Reach-1,1
Up Type=0
Dn Type=3
Dn Slope=0.005
Boundary for River Rch & Prof#=Chimney Creek 10,Reach-1,2
Up Type=0
Dn Type=3
Dn Slope=0.005
Boundary for River Rch & Prof#=Chimney Creek 10,Reach-1,3
Up Type=0
Dn Type=3
Dn Slope=0.005
Boundary for River Rch & Prof#=Chimney Creek 10,Reach-1,4
Up Type=0
Dn Type=3
Dn Slope=0.005
Boundary for River Rch & Prof#=Chimney Creek 10,Reach-1,5
Up Type=0
Dn Type=3
Dn Slope=0.005
Boundary for River Rch & Prof#=Chimney Creek 10,Reach-1,6
Up Type=0
Dn Type=3
Dn Slope=0.005
Boundary for River Rch & Prof#=Chimney Creek 10,Reach-1,7
Up Type=0
Dn Type=3
Dn Slope=0.005

--- Chimney Creek 1098.g01 (geometry) ---

Geom Title=Existing Conditions

River Reach=Chimney Creek 10,Reach-1
Reach XY= 30
      1670005.00      6926738.00      1669956.45      6926734.29
      1669873.80      6926688.02      1669849.24      6926731.90
      1669757.36      6926782.37      1669677.63      6926788.42
      1669621.47      6926755.13      1669596.97      6926681.64
      1669549.29      6926639.89      1669465.56      6926639.10
      1669399.02      6926685.64      1669302.56      6926693.52
      1669207.05      6926793.84      1669201.26      6927036.47
      1669149.05      6927132.24      1669111.00      6927143.81
      1669094.31      6927197.81      1669039.96      6927237.66
      1668820.22      6927237.48      1668749.47      6927190.39
      1668606.46      6927184.46      1668510.54      6927090.38
      1668497.28      6926991.00      1668415.67      6926989.05
      1668349.03      6927035.83      1668260.48      6927035.92
      1668098.97      6926889.62      1668056.75      6926891.34
      1667994.52      6926936.81      1667855.00      6926938.00

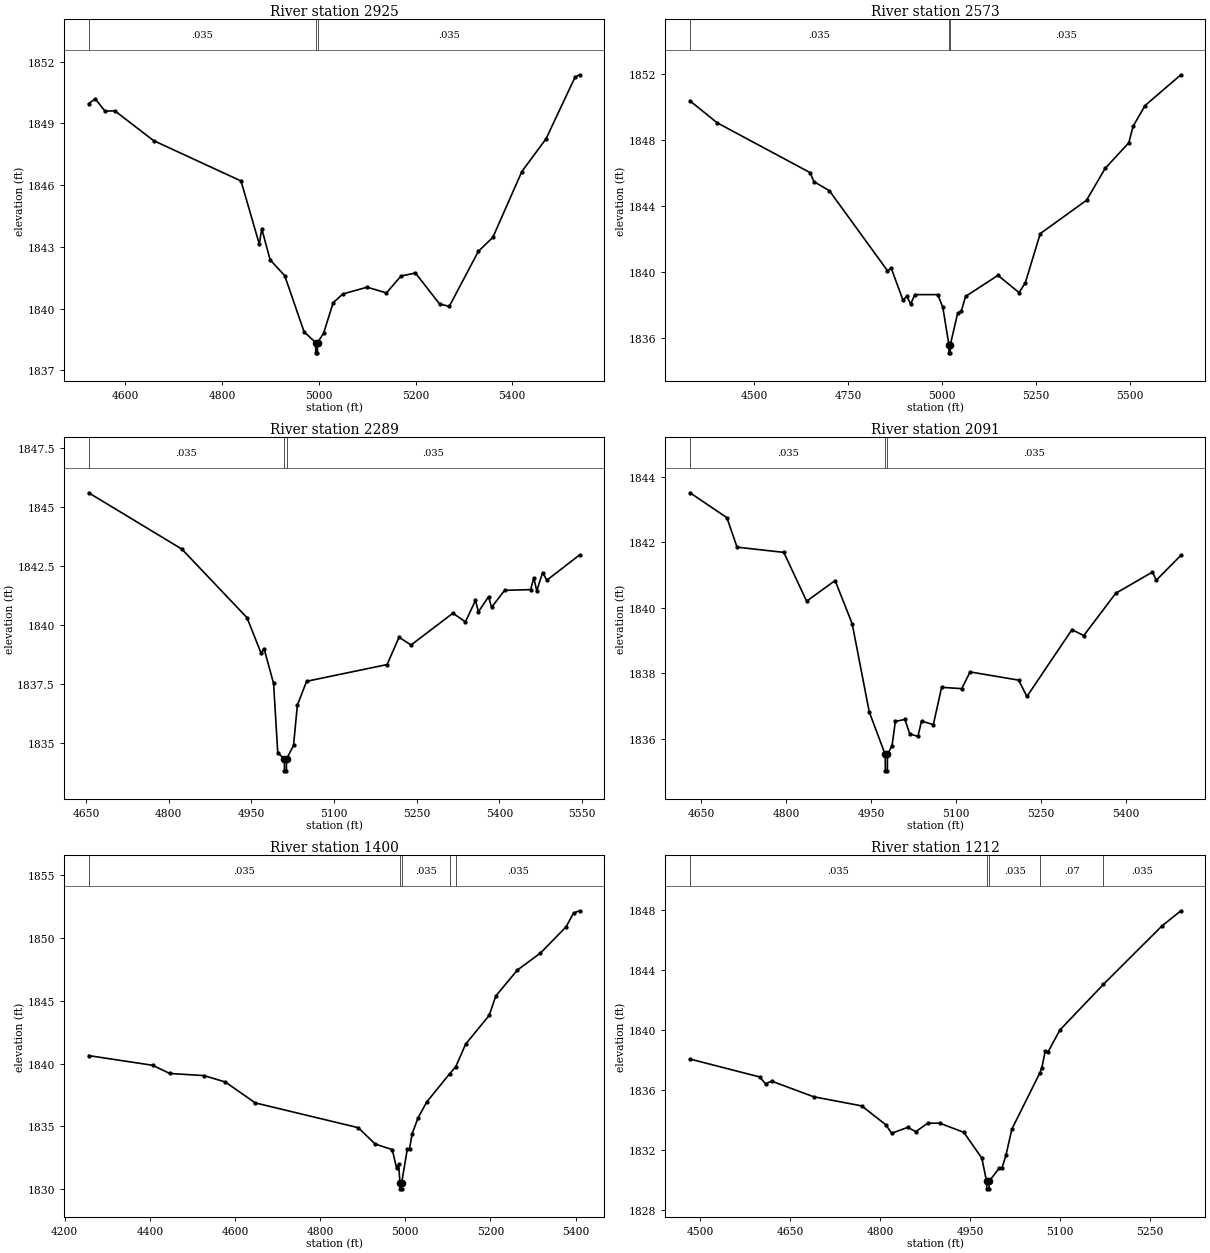
Type RM Length L Ch R = 1,2925,352,352,352
BEGIN DESCRIPTION:
Chimney Creek 1098 4.0
END DESCRIPTION:
XS GIS Cut Line= 3
      1670020.52      6926264.21      1669979.67      6926738.25
      1669973.64      6927277.21
#Sta/Elev= 30
  4524.2 1849.96  4538.0 1850.19  4558.1 1849.59  4578.2 1849.61  4658.5 1848.16
  4839.2 1846.20  4877.0 1843.13  4882.0 1843.88  4899.4 1842.37  4929.5 1841.60
  4969.6 1838.87  4993.4 1838.35  4993.7 1837.85  4997.2 1837.85  4997.4 1838.35
  5009.8 1838.80  5029.8 1840.29  5049.8 1840.71  5099.8 1841.04  5139.8 1840.76
  5169.8 1841.58  5199.8 1841.73  5249.8 1840.22  5269.8 1840.11  5329.8 1842.78
  5359.8 1843.46  5419.8 1846.66  5469.8 1848.25  5529.8 1851.25  5539.0 1851.36
#Mann=3,-1,0
  4524.2   0.035       0  4993.4   0.035       0  4997.4   0.035       0
Bank Sta=4993.4,4997.4
Exp/Cntr=0.3,0.1

Type RM Length L Ch R = 1,2573,284,284,284
BEGIN DESCRIPTION:
Chimney Creek 1098 3.0
END DESCRIPTION:
XS GIS Cut Line= 3
      1669855.00      6926138.00      1669691.23      6926788.81
      1669905.01      6927388.02
#Sta/Elev= 30
  4328.9 1850.36  4401.1 1849.03  4648.6 1846.01  4658.9 1845.46  4700.1 1844.91
  4854.8 1840.06  4865.1 1840.20  4896.0 1838.28  4906.4 1838.50  4916.7 1838.04
  4927.6 1838.61  4988.8 1838.61  5002.2 1837.84  5018.4 1835.58  5018.6 1835.08
  5022.1 1835.08  5022.4 1835.58  5041.6 1837.47  5051.4 1837.61  5062.8 1838.50
  5149.1 1839.78  5205.4 1838.73  5222.1 1839.34  5261.7 1842.31  5384.9 1844.33
  5434.4 1846.26  5497.6 1847.82  5508.8 1848.81  5540.6 1850.07  5636.2 1851.94
#Mann=3,-1,0
  4328.9   0.035       0  5018.4   0.035       0  5022.4   0.035       0
Bank Sta=5018.4,5022.4
Exp/Cntr=0.3,0.1

Type RM Length L Ch R = 1,2289,198,198,198
BEGIN DESCRIPTION:
Mapping XS 31bf591e
END DESCRIPTION:
XS GIS Cut Line= 3
      1669605.89      6926311.78      1669490.42      6926637.30
      1669702.18      6927139.70
#Sta/Elev= 30
  4654.6 1845.62  4823.7 1843.23  4941.9 1840.32  4967.5 1838.81  4972.8 1839.01
  4990.1 1837.53  4997.7 1834.59  5009.6 1834.32  5009.9 1833.82  5013.4 1833.82
  5013.6 1834.32  5026.3 1834.90  5033.3 1836.61  5050.0 1837.62  5196.1 1838.33
  5217.8 1839.49  5239.5 1839.16  5315.5 1840.51  5338.1 1840.14  5356.4 1841.05
  5361.8 1840.57  5380.1 1841.21  5385.6 1840.76  5409.3 1841.48  5456.5 1841.51
  5462.2 1842.01  5467.6 1841.46  5478.2 1842.23  5485.9 1841.91  5545.2 1842.98
#Mann=3,-1,0
  4654.6   0.035       0  5009.6   0.035       0  5013.6   0.035       0
Bank Sta=5009.6,5013.6
Exp/Cntr=0.3,0.1

Type RM Length L Ch R = 1,2091,691,691,691
BEGIN DESCRIPTION:
Mapping XS 6cbe30c2
END DESCRIPTION:
XS GIS Cut Line= 3
      1669349.30      6926323.23      1669308.93      6926694.34
      1669599.93      6927093.16
#Sta/Elev= 30
  4630.4 1843.51  4695.6 1842.75  4713.5 1841.85  4796.1 1841.69  4836.4 1840.20
  4886.7 1840.83  4916.9 1839.51  4947.0 1836.82  4975.2 1835.52  4975.5 1835.02
  4979.0 1835.02  4979.2 1835.52  4987.3 1835.79  4993.1 1836.53  5010.0 1836.59
  5018.5 1836.15  5033.0 1836.07  5039.3 1836.54  5060.2 1836.43  5074.8 1837.57
  5110.4 1837.53  5125.1 1838.04  5210.8 1837.79  5225.5 1837.29  5305.0 1839.33
  5325.9 1839.15  5382.3 1840.44  5447.2 1841.09  5453.9 1840.84  5497.4 1841.60
#Mann=3,-1,0
  4630.4   0.035       0  4975.2   0.035       0  4979.2   0.035       0
Bank Sta=4975.2,4979.2
Exp/Cntr=0.3,0.1

Type RM Length L Ch R = 1,1400,188,188,188
BEGIN DESCRIPTION:
Mapping XS eda1402b
END DESCRIPTION:
XS GIS Cut Line= 3
      1669093.43      6926498.60      1669017.91      6927243.39
      1669085.63      6927641.87
#Sta/Elev= 30
  4256.3 1840.63  4406.5 1839.86  4446.7 1839.21  4527.1 1839.04  4577.3 1838.53
  4647.7 1836.87  4889.5 1834.90  4929.1 1833.60  4969.3 1833.16  4979.3 1831.72
  4984.3 1831.98  4987.3 1830.54  4987.6 1830.04  4991.2 1830.04  4991.5 1830.54
  5004.7 1833.22  5009.8 1833.22  5016.0 1834.42  5029.9 1835.68  5050.2 1836.94
  5103.9 1839.18  5118.4 1839.74  5141.6 1841.54  5196.8 1843.82  5212.5 1845.37
  5263.2 1847.43  5317.4 1848.78  5377.7 1850.87  5395.0 1851.96  5409.1 1852.14
#Mann=5,-1,0
  4256.3   0.035       0  4987.3   0.035       0  4991.5   0.035       0
  5103.9    0.07       0  5118.4   0.035       0
Bank Sta=4987.3,4991.5
Exp/Cntr=0.3,0.1

Type RM Length L Ch R = 1,1212,241,241,241
BEGIN DESCRIPTION:
Mapping XS 65a2606e
END DESCRIPTION:
XS GIS Cut Line= 3
      1668861.88      6926722.16      1668830.63      6927241.65
      1668828.03      6927539.81
#Sta/Elev= 30
  4483.0 1838.06  4599.0 1836.87  4609.1 1836.41  4619.1 1836.59  4689.2 1835.55
  4769.4 1834.94  4809.4 1833.69  4819.4 1833.12  4846.0 1833.51  4859.5 1833.23
  4879.6 1833.79  4899.6 1833.79  4939.7 1833.18  4969.7 1831.46  4977.6 1829.92
  4977.9 1829.42  4981.5 1829.42  4981.8 1829.92  4999.1 1830.82  5003.4 1830.82
  5009.8 1831.64  5019.8 1833.40  5066.7 1837.16  5069.8 1837.49  5075.3 1838.58
  5080.3 1838.55  5099.8 1839.99  5172.4 1843.03  5269.8 1846.91  5301.6 1847.93
#Mann=5,-1,0
  4483.0   0.035       0  4977.6   0.035       0  4981.8   0.035       0
  5066.7    0.07       0  5172.4   0.035       0
Bank Sta=4977.6,4981.8
Exp/Cntr=0.3,0.1

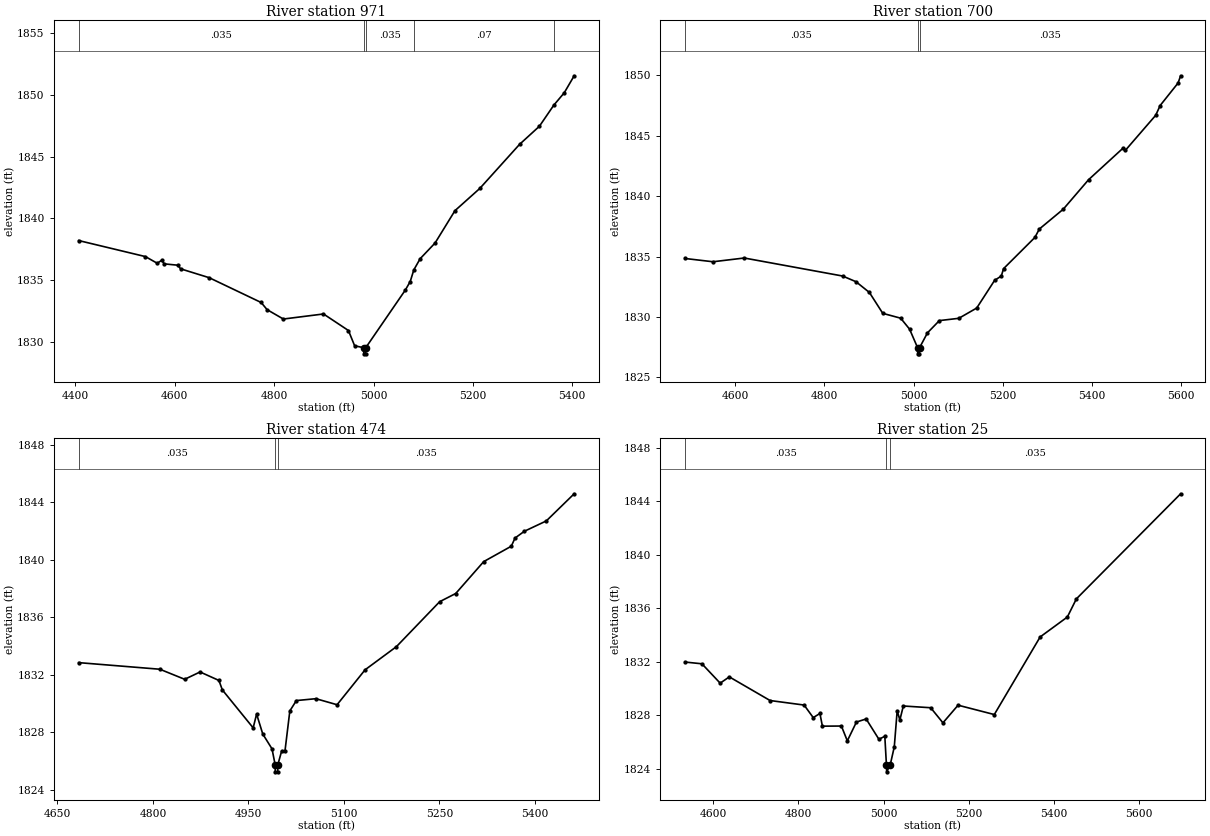
Type RM Length L Ch R = 1,971,271,271,271
BEGIN DESCRIPTION:
Chimney Creek 1098 2.0
END DESCRIPTION:
XS GIS Cut Line= 3
      1668780.08      6926616.76      1668605.00      6927188.00
      1668605.00      6927588.03
#Sta/Elev= 30
  4406.4 1838.20  4540.8 1836.90  4564.6 1836.36  4573.6 1836.60  4578.8 1836.31
  4606.3 1836.20  4611.5 1835.91  4669.2 1835.19  4773.8 1833.18  4785.8 1832.60
  4818.5 1831.84  4899.3 1832.25  4949.5 1830.91  4962.0 1829.67  4980.2 1829.52
  4980.4 1829.02  4984.1 1829.02  4984.4 1829.52  5063.9 1834.18  5073.9 1834.88
  5081.1 1835.82  5093.9 1836.73  5123.9 1838.00  5163.9 1840.62  5213.9 1842.42
  5293.9 1845.99  5333.9 1847.46  5363.1 1849.18  5383.9 1850.17  5403.9 1851.55
#Mann=5,-1,0
  4406.4   0.035       0  4980.2   0.035       0  4984.4   0.035       0
  5081.1    0.07       0  5363.1   0.035       0
Bank Sta=4980.2,4984.4
Exp/Cntr=0.3,0.1

Type RM Length L Ch R = 1,700,226,226,226
BEGIN DESCRIPTION:
Mapping XS daab0b27
END DESCRIPTION:
XS GIS Cut Line= 3
      1668492.30      6926475.64      1668464.09      6926989.92
      1668420.74      6927583.78
#Sta/Elev= 30
  4487.9 1834.84  4550.4 1834.57  4620.5 1834.88  4840.8 1833.39  4870.8 1832.92
  4900.9 1832.03  4930.9 1830.30  4971.0 1829.90  4991.0 1828.99  5009.0 1827.45
  5009.2 1826.95  5012.9 1826.95  5013.2 1827.45  5031.1 1828.69  5057.7 1829.70
  5101.3 1829.89  5141.4 1830.74  5181.5 1833.03  5196.5 1833.39  5201.6 1834.00
  5271.7 1836.58  5281.8 1837.28  5335.4 1838.92  5392.1 1841.36  5469.3 1843.97
  5474.3 1843.78  5542.5 1846.69  5552.5 1847.50  5592.6 1849.36  5598.4 1849.96
#Mann=3,-1,0
  4487.9   0.035       0  5009.0   0.035       0  5013.2   0.035       0
Bank Sta=5009,5013.2
Exp/Cntr=0.3,0.1

Type RM Length L Ch R = 1,474,449,449,449
BEGIN DESCRIPTION:
Mapping XS 47fa1cb5
END DESCRIPTION:
XS GIS Cut Line= 3
      1668372.48      6926739.54      1668252.68      6927038.17
      1668349.56      6927484.52
#Sta/Elev= 30
  4683.2 1832.83  4810.8 1832.37  4849.8 1831.67  4874.0 1832.18  4903.6 1831.59
  4909.0 1830.93  4957.4 1828.29  4962.8 1829.25  4972.5 1827.86  4987.0 1826.83
  4991.9 1825.73  4992.2 1825.23  4995.9 1825.23  4996.2 1825.73  5002.2 1826.69
  5007.4 1826.69  5015.0 1829.47  5025.3 1830.19  5055.9 1830.32  5089.2 1829.90
  5133.2 1832.33  5182.4 1833.94  5250.4 1837.07  5275.6 1837.64  5319.6 1839.86
  5362.9 1840.93  5368.8 1841.50  5383.4 1841.97  5417.9 1842.69  5461.7 1844.58
#Mann=3,-1,0
  4683.2   0.035       0  4991.9   0.035       0  4996.2   0.035       0
Bank Sta=4991.9,4996.2
Exp/Cntr=0.3,0.1

Type RM Length L Ch R = 1,25,0,0,0
BEGIN DESCRIPTION:
Chimney Creek 1098 1.0
END DESCRIPTION:
XS GIS Cut Line= 3
      1668280.73      6926700.99      1667880.00      6926938.06
      1668309.38      6927487.48
#Sta/Elev= 30
  4534.4 1831.97  4573.9 1831.84  4616.7 1830.39  4638.2 1830.86  4733.8 1829.09
  4813.7 1828.75  4835.1 1827.81  4850.8 1828.12  4856.6 1827.17  4901.2 1827.18
  4915.1 1826.07  4936.5 1827.48  4959.3 1827.71  4989.2 1826.19  5003.1 1826.41
  5006.9 1824.25  5007.4 1823.75  5015.6 1824.25  5025.3 1825.62  5032.1 1828.33
  5038.4 1827.63  5046.5 1828.68  5110.7 1828.55  5139.5 1827.42  5175.0 1828.74
  5260.0 1828.04  5367.6 1833.85  5431.4 1835.34  5452.6 1836.70  5697.3 1844.57
#Mann=3,-1,0
  4534.4   0.035       0  5006.9   0.035       0  5015.6   0.035       0
Bank Sta=5006.9,5015.6
Exp/Cntr=0.3,0.1

Chan Stop Cuts=-1