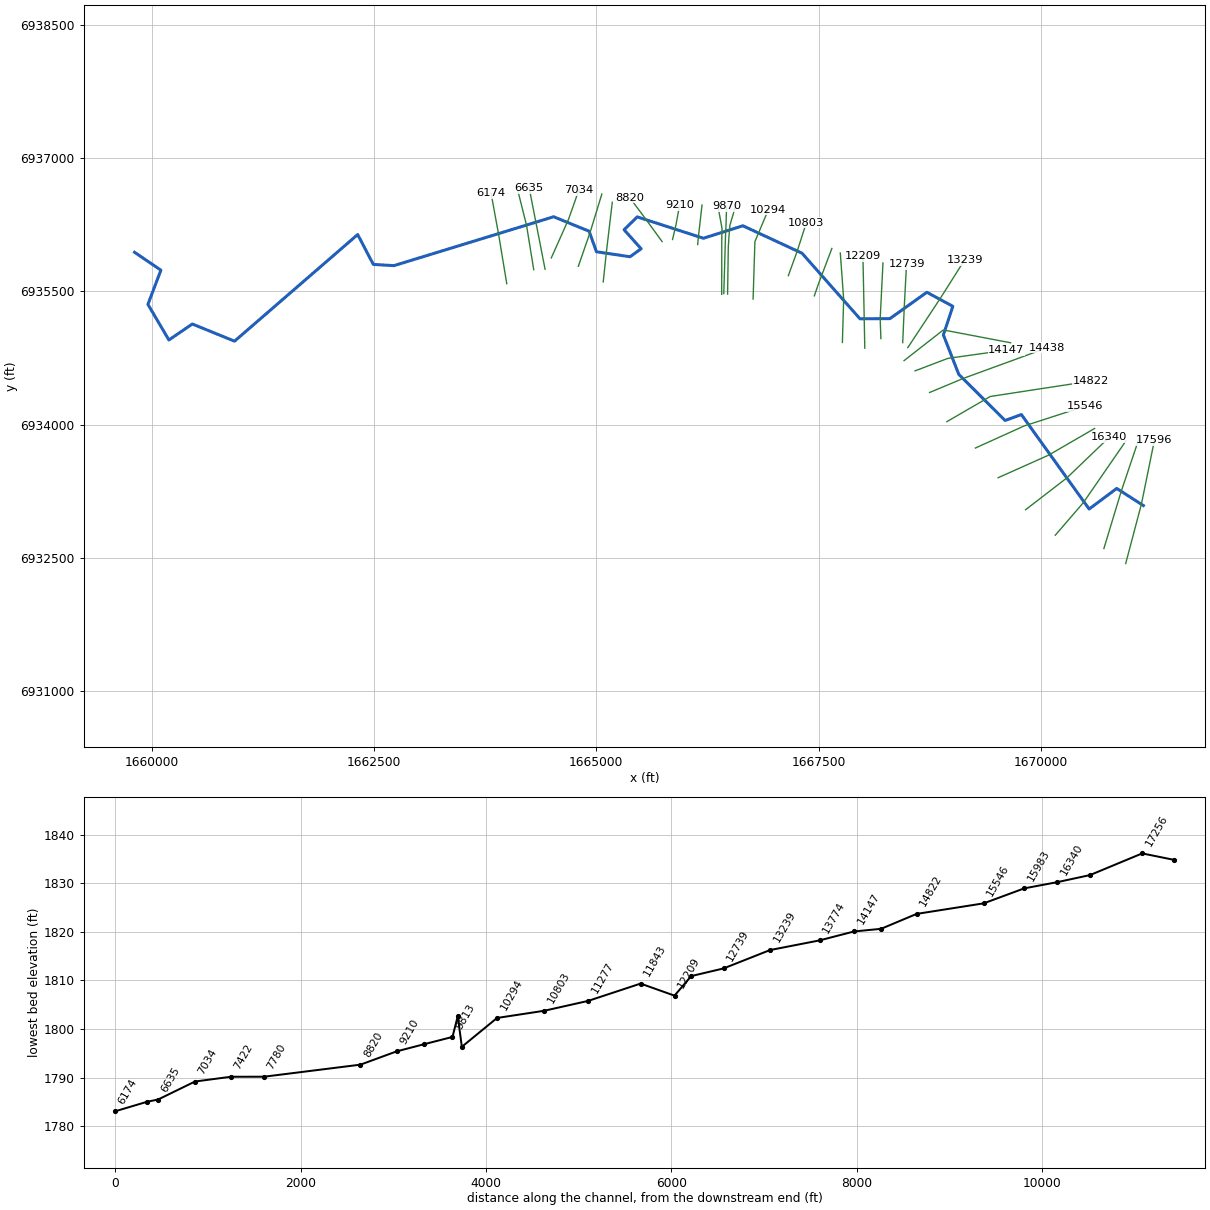
--- Chimney Creek 1099.prj (project) ---

Proj Title=Chimney Creek 1099 Base Level Engineering
Current Plan=p01
Default Exp/Contr=0.3,0.1
English Units
Geom File=g01
Flow File=f01
Plan File=p01
BEGIN DESCRIPTION:
Chimney Creek 1099
END DESCRIPTION:

--- Chimney Creek 1099.p01 (plan) ---

Plan Title=Multiple Run
Short Identifier=Multiple
Geom File=g01
Flow File=f01
Subcritical Flow
K Sum by GR= 0
Std Step Tol= 0.01
Critical Tol= 0.01
Num of Std Step Trials= 20
Max Error Tol= 0.3
Flow Tol Ratio= 0.001
Split Flow NTrial= 30
Split Flow Tol= 0.02
Split Flow Ratio= 0.02
Log Output Level= 0
Friction Slope Method= 1
Unsteady Friction Slope Method= 2
Unsteady Bridges Friction Slope Method= 1
Parabolic Critical Depth
Global Vel Dist=  1 , 1 , 1
Global Log Level= 0
CheckData=True
Encroach Param= -1, 0, 0, 0
BEGIN DESCRIPTION:
Multiple Run
END DESCRIPTION:

--- Chimney Creek 1099.f01 (steady flow) ---

Flow Title=Multiple
Number of Profiles=7
Profile Names=10-year,25-year,50-year,1pct_min,100-year,1pct_plu,500-year
River Rch & RM= Chimney Creek 10,Reach-1,17596
     262     364     449     276     550    1097     836
River Rch & RM= Chimney Creek 10,Reach-1,17256
     368     517     642     396     790    1576    1214
River Rch & RM= Chimney Creek 10,Reach-1,6635
     395     556     691     427     852    1701    1313
River Rch & RM= Chimney Creek 10,Reach-1,2250
     561     804    1011     631    1260    2513    1983
River Rch & RM= Chimney Creek 10,Reach-1,13
    1056    1552    1985    1258    2511    5010    4073
Boundary for River Rch & Prof#=Chimney Creek 10,Reach-1,1
Up Type=0
Dn Type=3
Dn Slope=0.005
Boundary for River Rch & Prof#=Chimney Creek 10,Reach-1,2
Up Type=0
Dn Type=3
Dn Slope=0.005
Boundary for River Rch & Prof#=Chimney Creek 10,Reach-1,3
Up Type=0
Dn Type=3
Dn Slope=0.005
Boundary for River Rch & Prof#=Chimney Creek 10,Reach-1,4
Up Type=0
Dn Type=3
Dn Slope=0.005
Boundary for River Rch & Prof#=Chimney Creek 10,Reach-1,5
Up Type=0
Dn Type=3
Dn Slope=0.005
Boundary for River Rch & Prof#=Chimney Creek 10,Reach-1,6
Up Type=0
Dn Type=3
Dn Slope=0.005
Boundary for River Rch & Prof#=Chimney Creek 10,Reach-1,7
Up Type=0
Dn Type=3
Dn Slope=0.005

--- Chimney Creek 1099.g01 (geometry) ---

Geom Title=Existing Conditions

River Reach=Chimney Creek 10,Reach-1
Reach XY= 30
      1671155.00      6933088.00      1670855.00      6933280.90
      1670544.95      6933049.08      1669782.27      6934112.16
      1669599.23      6934045.33      1669078.01      6934564.53
      1668904.93      6935008.01      1669011.43      6935329.96
      1668719.08      6935487.78      1668303.55      6935191.53
      1667966.53      6935189.50      1667314.68      6935927.24
      1666649.16      6936235.95      1666205.01      6936095.53
      1665460.85      6936335.94      1665312.59      6936191.33
      1665504.47      6935977.31      1665380.01      6935887.58
      1665002.26      6935943.34      1664918.81      6936174.65
      1664520.22      6936337.50      1662723.34      6935787.61
      1662491.33      6935801.22      1662315.71      6936137.30
      1660930.10      6934937.76      1660455.00      6935130.93
      1660191.76      6934951.10      1659955.52      6935351.86
      1660101.54      6935736.50      1659805.00      6935938.00

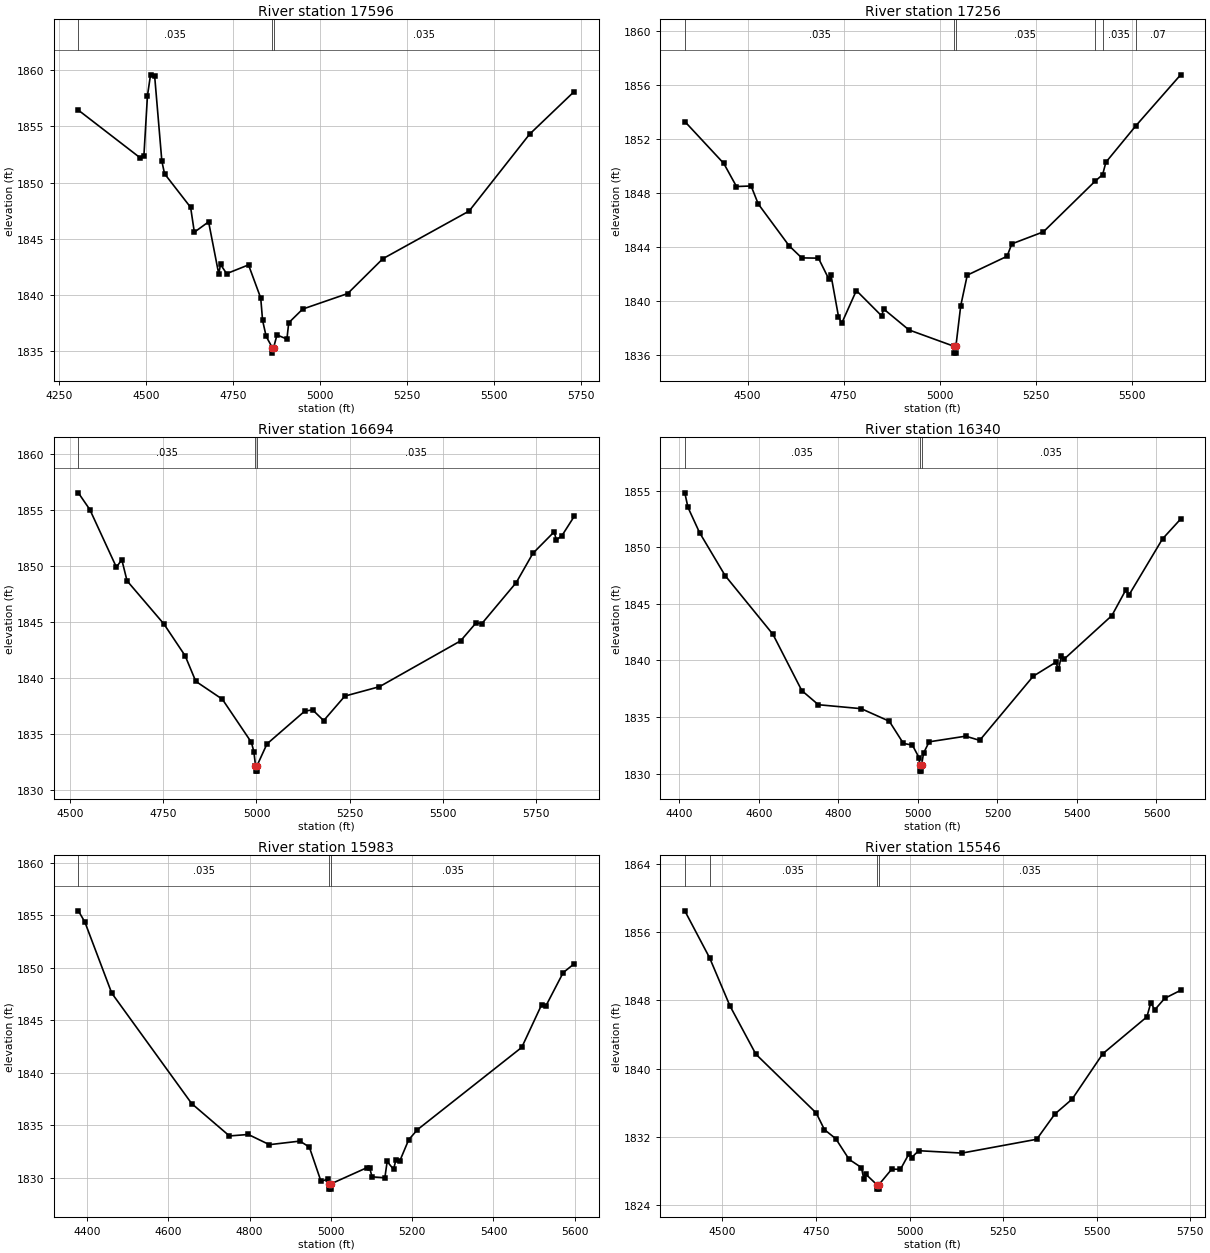
Type RM Length L Ch R = 1,17596,340,340,340
BEGIN DESCRIPTION:
Chimney Creek 1099 29.0
END DESCRIPTION:
XS GIS Cut Line= 3
      1670956.01      6932435.80      1671133.78      6933108.40
      1671279.20      6933823.87
#Sta/Elev= 30
  4304.3 1856.44  4482.4 1852.19  4492.8 1852.36  4503.1 1857.73  4511.9 1859.58
  4523.8 1859.46  4544.5 1851.89  4552.2 1850.78  4627.2 1847.79  4637.9 1845.58
  4678.9 1846.50  4708.0 1841.87  4713.2 1842.71  4730.7 1841.89  4793.7 1842.67
  4828.8 1839.72  4834.1 1837.74  4844.4 1836.31  4861.8 1835.32  4862.1 1834.82
  4866.0 1835.32  4875.5 1836.44  4904.1 1836.07  4909.3 1837.52  4949.5 1838.74
  5078.8 1840.12  5180.0 1843.22  5428.0 1847.46  5601.7 1854.29  5730.1 1858.09
#Mann=3,-1,0
  4304.3   0.035       0  4861.8   0.035       0  4866.0   0.035       0
Bank Sta=4861.8,4866
Exp/Cntr=0.3,0.1

Type RM Length L Ch R = 1,17256,562,562,562
BEGIN DESCRIPTION:
Mapping XS 5046e8c5
END DESCRIPTION:
XS GIS Cut Line= 3
      1670710.80      6932605.12      1670903.93      6933243.10
      1671103.15      6933834.26
#Sta/Elev= 30
  4336.6 1853.30  4438.1 1850.19  4471.1 1848.48  4509.2 1848.52  4527.7 1847.19
  4608.0 1844.09  4640.9 1843.19  4684.4 1843.17  4712.0 1841.59  4717.2 1841.89
  4736.6 1838.84  4744.9 1838.34  4783.1 1840.77  4848.9 1838.89  4854.2 1839.40
  4920.0 1837.85  5037.9 1836.63  5038.2 1836.13  5041.9 1836.13  5042.1 1836.63
  5054.7 1839.64  5071.7 1841.91  5175.3 1843.31  5187.7 1844.23  5269.8 1845.12
  5403.9 1848.86  5424.0 1849.36  5432.5 1850.28  5509.8 1852.96  5627.0 1856.76
#Mann=6,-1,0
  4336.6   0.035       0  5037.9   0.035       0  5042.1   0.035       0
  5403.9    0.07       0  5424.0   0.035       0  5509.8    0.07       0
Bank Sta=5037.9,5042.1
Exp/Cntr=0.3,0.1

Type RM Length L Ch R = 1,16694,354,354,354
BEGIN DESCRIPTION:
Mapping XS a80bdf0e
END DESCRIPTION:
XS GIS Cut Line= 3
      1670163.92      6932754.82      1670478.58      6933119.40
      1670960.15      6933817.89
#Sta/Elev= 30
  4522.1 1856.53  4553.0 1855.03  4624.3 1849.88  4638.6 1850.57  4652.8 1848.67
  4751.6 1844.82  4808.6 1841.98  4837.1 1839.70  4908.4 1838.10  4986.3 1834.25
  4992.9 1833.43  4997.3 1832.18  4997.6 1831.68  5001.3 1831.68  5001.6 1832.18
  5028.1 1834.11  5129.5 1837.04  5150.5 1837.15  5180.2 1836.19  5237.0 1838.38
  5329.9 1839.22  5547.4 1843.31  5589.3 1844.93  5604.2 1844.84  5696.8 1848.52
  5741.5 1851.13  5798.3 1853.04  5804.4 1852.33  5819.2 1852.70  5852.1 1854.42
#Mann=3,-1,0
  4522.1   0.035       0  4997.3   0.035       0  5001.6   0.035       0
Bank Sta=4997.3,5001.6
Exp/Cntr=0.3,0.1

Type RM Length L Ch R = 1,16340,357,357,357
BEGIN DESCRIPTION:
Mapping XS 7ecaf869
END DESCRIPTION:
XS GIS Cut Line= 3
      1669829.68      6933041.25      1670294.12      6933399.35
      1670770.77      6933856.50
#Sta/Elev= 30
  4413.9 1854.82  4421.8 1853.54  4450.9 1851.31  4515.2 1847.51  4635.6 1842.31
  4708.1 1837.34  4749.8 1836.09  4857.6 1835.74  4928.2 1834.63  4963.6 1832.67
  4986.2 1832.52  5003.0 1831.41  5004.9 1830.72  5005.2 1830.22  5008.9 1830.22
  5009.2 1830.72  5014.3 1831.81  5028.4 1832.81  5120.3 1833.31  5155.5 1832.94
  5290.1 1838.61  5346.7 1839.84  5353.6 1839.24  5360.9 1840.36  5367.8 1840.12
  5487.9 1843.97  5523.5 1846.27  5530.4 1845.76  5615.3 1850.75  5660.8 1852.50
#Mann=3,-1,0
  4413.9   0.035       0  5004.9   0.035       0  5009.2   0.035       0
Bank Sta=5004.9,5009.2
Exp/Cntr=0.3,0.1

Type RM Length L Ch R = 1,15983,437,437,437
BEGIN DESCRIPTION:
Mapping XS 3e3ca9cd
END DESCRIPTION:
XS GIS Cut Line= 3
      1669520.42      6933401.49      1670088.13      6933654.96
      1670605.53      6933955.33
#Sta/Elev= 30
  4378.5 1855.42  4394.5 1854.36  4460.7 1847.59  4657.4 1837.08  4750.3 1834.00
  4796.7 1834.14  4848.6 1833.17  4923.7 1833.51  4946.9 1832.94  4975.6 1829.68
  4993.4 1829.91  4995.6 1829.44  4995.9 1828.94  4999.7 1828.94  5000.0 1829.44
  5089.1 1830.99  5095.4 1830.95  5101.2 1830.11  5132.7 1830.02  5138.4 1831.57
  5154.2 1830.82  5160.0 1831.75  5169.9 1831.66  5191.4 1833.64  5213.0 1834.60
  5469.6 1842.43  5518.5 1846.49  5528.4 1846.33  5571.5 1849.54  5598.5 1850.38
#Mann=3,-1,0
  4378.5   0.035       0  4995.6   0.035       0  5000.0   0.035       0
Bank Sta=4995.6,5000
Exp/Cntr=0.3,0.1

Type RM Length L Ch R = 1,15546,724,724,724
BEGIN DESCRIPTION:
Mapping XS 5f1629ee
END DESCRIPTION:
XS GIS Cut Line= 3
      1669265.23      6933735.70      1669813.83      6933983.96
      1670500.68      6934205.97
#Sta/Elev= 30
  4399.8 1858.52  4466.2 1852.99  4520.3 1847.37  4589.5 1841.70  4750.8 1834.79
  4772.7 1832.84  4802.9 1831.78  4838.6 1829.35  4871.5 1828.39  4877.7 1827.06
  4883.2 1827.61  4913.2 1826.36  4913.5 1825.86  4917.3 1825.86  4917.6 1826.36
  4952.5 1828.21  4975.6 1828.18  4998.7 1830.03  5005.2 1829.55  5024.2 1830.37
  5139.8 1830.09  5339.5 1831.71  5387.9 1834.67  5434.1 1836.42  5516.0 1841.75
  5633.8 1846.08  5644.1 1847.73  5654.8 1846.91  5681.3 1848.25  5723.8 1849.19
#Mann=4,-1,0
  4399.8    0.07       0  4466.2   0.035       0  4913.2   0.035       0
  4917.6   0.035       0
Bank Sta=4913.2,4917.6
Exp/Cntr=0.3,0.1

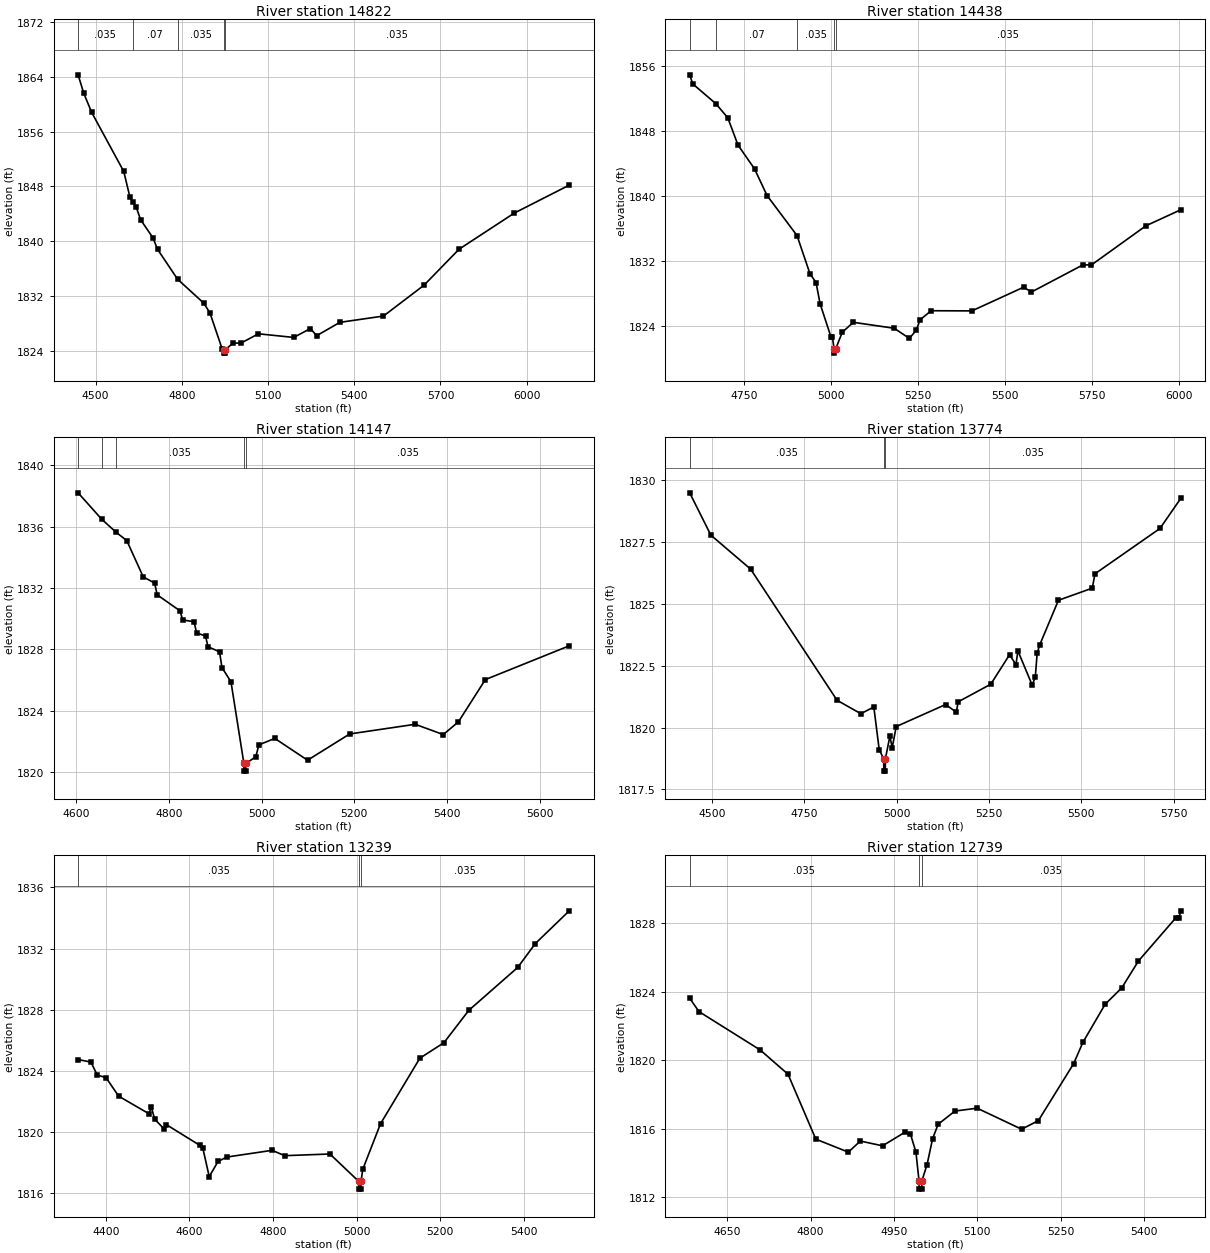
Type RM Length L Ch R = 1,14822,384,384,384
BEGIN DESCRIPTION:
Mapping XS c51e769f
END DESCRIPTION:
XS GIS Cut Line= 3
      1668944.24      6934032.32      1669432.11      6934315.32
      1670564.06      6934488.93
#Sta/Elev= 30
  4439.1 1864.29  4458.9 1861.59  4486.2 1858.82  4598.0 1850.19  4619.5 1846.44
  4629.3 1845.75  4641.0 1845.02  4656.8 1843.14  4699.8 1840.50  4715.6 1838.83
  4785.4 1834.47  4876.2 1830.99  4897.7 1829.58  4940.8 1824.25  4946.4 1824.19
  4946.7 1823.69  4950.6 1823.69  4950.9 1824.19  4978.1 1825.13  5007.1 1825.18
  5066.7 1826.51  5189.4 1825.98  5247.7 1827.28  5269.1 1826.23  5350.0 1828.18
  5501.8 1829.10  5642.9 1833.60  5764.8 1838.85  5957.0 1844.12  6148.3 1848.20
#Mann=5,-1,0
  4439.1   0.035       0  4629.3    0.07       0  4785.4   0.035       0
  4946.4   0.035       0  4950.9   0.035       0
Bank Sta=4946.4,4950.9
Exp/Cntr=0.3,0.1

Type RM Length L Ch R = 1,14438,291,291,291
BEGIN DESCRIPTION:
Mapping XS 1fc8dcda
END DESCRIPTION:
XS GIS Cut Line= 3
      1668749.80      6934360.45      1669128.29      6934518.45
      1670069.22      6934862.18
#Sta/Elev= 30
  4592.8 1854.95  4601.6 1853.83  4668.0 1851.39  4702.3 1849.65  4731.6 1846.29
  4779.2 1843.35  4815.2 1840.06  4901.4 1835.12  4938.3 1830.44  4956.0 1829.33
  4967.6 1826.72  4998.5 1822.67  5002.9 1822.67  5007.8 1821.12  5008.1 1820.62
  5012.3 1821.12  5031.4 1823.20  5063.3 1824.42  5180.4 1823.69  5224.3 1822.44
  5244.2 1823.45  5255.0 1824.73  5286.9 1825.85  5404.0 1825.83  5553.1 1828.76
  5574.8 1828.15  5723.4 1831.51  5747.4 1831.49  5904.4 1836.33  6004.7 1838.31
#Mann=5,-1,0
  4592.8   0.035       0  4668.0    0.07       0  4901.4   0.035       0
  5007.8   0.035       0  5012.3   0.035       0
Bank Sta=5007.8,5012.3
Exp/Cntr=0.3,0.1

Type RM Length L Ch R = 1,14147,373,373,373
BEGIN DESCRIPTION:
Mapping XS 8bc9f8c5
END DESCRIPTION:
XS GIS Cut Line= 3
      1668586.57      6934603.85      1668956.35      6934744.47
      1669614.33      6934836.48
#Sta/Elev= 30
  4604.2 1838.20  4655.5 1836.47  4686.7 1835.62  4709.3 1835.09  4744.7 1832.73
  4769.5 1832.32  4774.8 1831.56  4824.4 1830.51  4829.7 1829.92  4854.5 1829.81
  4859.8 1829.09  4879.2 1828.87  4884.6 1828.18  4909.4 1827.85  4914.7 1826.82
  4934.1 1825.90  4962.0 1820.58  4962.3 1820.08  4966.2 1820.08  4966.5 1820.58
  4987.7 1821.02  4994.4 1821.79  5028.7 1822.21  5099.4 1820.79  5190.3 1822.50
  5331.7 1823.13  5392.3 1822.46  5425.0 1823.29  5483.1 1826.04  5664.2 1828.24
#Mann=5,-1,0
  4604.2   0.035       0  4655.5    0.07       0  4686.7   0.035       0
  4962.0   0.035       0  4966.5   0.035       0
Bank Sta=4962,4966.5
Exp/Cntr=0.3,0.1

Type RM Length L Ch R = 1,13774,535,535,535
BEGIN DESCRIPTION:
Mapping XS 4e063ffb
END DESCRIPTION:
XS GIS Cut Line= 3
      1668462.90      6934719.30      1668904.26      6935063.91
      1669660.62      6934919.93
#Sta/Elev= 30
  4439.8 1829.48  4497.1 1827.77  4604.7 1826.40  4838.9 1821.10  4903.2 1820.56
  4938.4 1820.83  4952.9 1819.11  4965.0 1818.74  4965.4 1818.24  4969.4 1818.24
  4969.7 1818.74  4981.8 1819.65  4988.2 1819.19  4999.0 1820.04  5132.8 1820.93
  5161.7 1820.62  5166.8 1821.04  5255.0 1821.75  5305.9 1822.94  5323.3 1822.54
  5328.4 1823.10  5367.0 1821.72  5375.5 1822.03  5380.6 1823.00  5387.3 1823.33
  5438.2 1825.14  5529.8 1825.63  5537.2 1826.21  5713.1 1828.04  5769.7 1829.26
#Mann=3,-1,0
  4439.8   0.035       0  4965.0   0.035       0  4969.7   0.035       0
Bank Sta=4965,4969.7
Exp/Cntr=0.3,0.1

Type RM Length L Ch R = 1,13239,500,500,500
BEGIN DESCRIPTION:
Mapping XS 84c56669
END DESCRIPTION:
XS GIS Cut Line= 3
      1668504.59      6934865.14      1668871.66      6935421.33
      1669143.51      6935851.30
#Sta/Elev= 30
  4333.6 1824.73  4364.3 1824.57  4379.3 1823.72  4400.4 1823.55  4430.5 1822.34
  4502.8 1821.19  4508.8 1821.62  4516.8 1820.83  4538.9 1820.20  4544.9 1820.47
  4624.6 1819.12  4632.2 1818.91  4647.3 1817.07  4668.4 1818.06  4689.4 1818.35
  4797.8 1818.79  4827.9 1818.44  4936.1 1818.55  5005.3 1816.75  5005.7 1816.25
  5010.1 1816.25  5010.5 1816.75  5014.7 1817.55  5057.1 1820.53  5151.2 1824.82
  5209.0 1825.84  5268.2 1827.95  5385.2 1830.76  5427.6 1832.33  5508.7 1834.47
#Mann=3,-1,0
  4333.6   0.035       0  5005.3   0.035       0  5010.5   0.035       0
Bank Sta=5005.3,5010.5
Exp/Cntr=0.3,0.1

Type RM Length L Ch R = 1,12739,350,350,350
BEGIN DESCRIPTION:
Mapping XS 899c22bb
END DESCRIPTION:
XS GIS Cut Line= 3
      1668447.40      6934921.20      1668465.63      6935339.21
      1668490.31      6935804.15
#Sta/Elev= 30
  4582.5 1823.63  4599.3 1822.85  4709.4 1820.61  4759.5 1819.19  4809.5 1815.40
  4868.1 1814.64  4889.6 1815.29  4929.6 1815.01  4969.7 1815.80  4979.7 1815.71
  4989.7 1814.64  4995.2 1812.98  4995.6 1812.48  5000.1 1812.48  5000.5 1812.98
  5009.7 1813.91  5019.7 1815.43  5029.7 1816.27  5059.8 1817.04  5099.8 1817.21
  5179.9 1815.98  5210.0 1816.48  5273.5 1819.81  5290.1 1821.05  5330.2 1823.28
  5360.2 1824.24  5390.2 1825.81  5458.0 1828.35  5463.0 1828.34  5466.5 1828.74
#Mann=3,-1,0
  4582.5   0.035       0  4995.2   0.035       0  5000.5   0.035       0
Bank Sta=4995.2,5000.5
Exp/Cntr=0.3,0.1

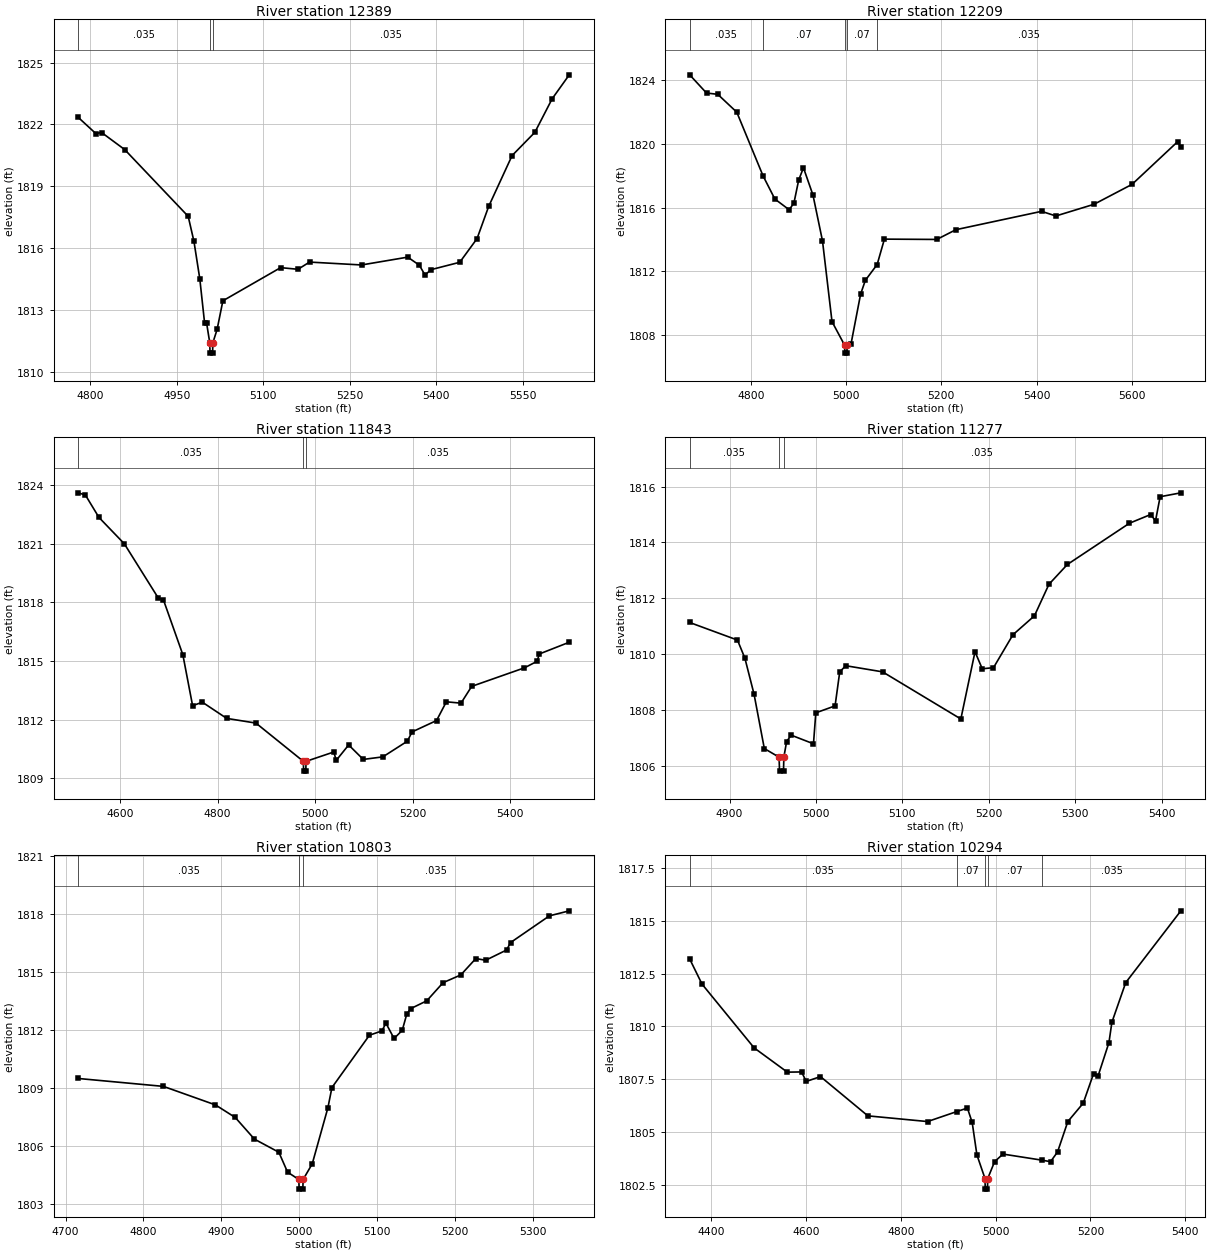
Type RM Length L Ch R = 1,12389,180,180,180
BEGIN DESCRIPTION:
Mapping XS 2fee466e
END DESCRIPTION:
XS GIS Cut Line= 3
      1668201.71      6934967.28      1668193.90      6935189.91
      1668225.15      6935817.56
#Sta/Elev= 30
  4779.2 1822.35  4809.9 1821.56  4819.9 1821.61  4860.0 1820.78  4970.0 1817.54
  4980.0 1816.32  4990.1 1814.51  4998.5 1812.34  5002.0 1812.34  5007.4 1811.40
  5007.8 1810.90  5012.3 1810.90  5012.7 1811.40  5020.1 1812.05  5030.1 1813.44
  5130.2 1815.05  5160.3 1814.97  5180.3 1815.32  5270.4 1815.18  5350.5 1815.56
  5370.5 1815.17  5380.5 1814.69  5390.5 1814.95  5440.6 1815.31  5470.6 1816.46
  5490.7 1818.02  5531.3 1820.49  5570.8 1821.62  5600.8 1823.25  5630.4 1824.41
#Mann=3,-1,0
  4779.2   0.035       0  5007.4   0.035       0  5012.7   0.035       0
Bank Sta=5007.4,5012.7
Exp/Cntr=0.3,0.1

Type RM Length L Ch R = 1,12209,366,366,366
BEGIN DESCRIPTION:
Mapping XS 0802b272
END DESCRIPTION:
XS GIS Cut Line= 3
      1668020.72      6934859.16      1668014.21      6935191.21
      1667999.89      6935890.44
#Sta/Elev= 30
  4671.6 1824.31  4706.9 1823.17  4730.5 1823.09  4770.5 1821.97  4825.7 1817.98
  4850.5 1816.53  4880.5 1815.86  4890.5 1816.28  4900.5 1817.72  4910.5 1818.49
  4930.5 1816.78  4950.5 1813.91  4970.5 1808.85  4996.9 1807.38  4997.4 1806.88
  5001.9 1806.88  5002.3 1807.38  5010.5 1807.47  5030.5 1810.57  5040.5 1811.44
  5065.3 1812.43  5080.5 1814.02  5190.5 1814.00  5230.6 1814.61  5410.6 1815.76
  5440.6 1815.47  5520.6 1816.20  5600.6 1817.45  5696.6 1820.13  5703.1 1819.77
#Mann=5,-1,0
  4671.6   0.035       0  4825.7    0.07       0  4996.9    0.07       0
  5002.3    0.07       0  5065.3   0.035       0
Bank Sta=4996.9,5002.3
Exp/Cntr=0.3,0.1

Type RM Length L Ch R = 1,11843,566,566,566
BEGIN DESCRIPTION:
Mapping XS eade644b
END DESCRIPTION:
XS GIS Cut Line= 3
      1667768.66      6934923.12      1667782.98      6935411.37
      1667745.22      6935929.64
#Sta/Elev= 30
  4513.6 1823.61  4528.5 1823.50  4556.4 1822.35  4608.5 1821.00  4678.5 1818.21
  4688.6 1818.14  4728.6 1815.32  4748.6 1812.71  4768.6 1812.89  4818.6 1812.06
  4878.6 1811.82  4976.0 1809.86  4976.4 1809.36  4981.0 1809.36  4981.4 1809.86
  5038.4 1810.34  5043.4 1809.91  5068.9 1810.70  5098.9 1809.96  5139.1 1810.09
  5189.2 1810.89  5199.2 1811.37  5249.3 1811.95  5269.4 1812.91  5299.5 1812.84
  5321.4 1813.70  5429.8 1814.65  5455.4 1814.98  5460.4 1815.36  5521.7 1815.96
#Mann=3,-1,0
  4513.6   0.035       0  4976.0   0.035       0  4981.4   0.035       0
Bank Sta=4976,4981.4
Exp/Cntr=0.3,0.1

Type RM Length L Ch R = 1,11277,474,474,474
BEGIN DESCRIPTION:
Mapping XS 66c5f621
END DESCRIPTION:
XS GIS Cut Line= 3
      1667452.97      6935447.62      1667501.73      6935588.02
      1667650.22      6935980.87
#Sta/Elev= 30
  4853.8 1811.13  4909.1 1810.50  4917.7 1809.85  4928.3 1808.56  4940.2 1806.61
  4957.3 1806.30  4957.8 1805.80  4962.4 1805.80  4962.8 1806.30  4966.0 1806.86
  4971.3 1807.09  4997.1 1806.78  4999.8 1807.89  5022.1 1808.14  5027.5 1809.36
  5034.5 1809.58  5077.1 1809.36  5167.7 1807.67  5184.1 1810.08  5192.5 1809.47
  5205.5 1809.51  5228.0 1810.69  5252.9 1811.37  5269.7 1812.50  5291.0 1813.21
  5362.9 1814.69  5387.3 1815.00  5393.1 1814.78  5398.4 1815.64  5422.4 1815.78
#Mann=3,-1,0
  4853.8   0.035       0  4957.3   0.035       0  4962.8   0.035       0
Bank Sta=4957.3,4962.8
Exp/Cntr=0.3,0.1

Type RM Length L Ch R = 1,10803,509,509,509
BEGIN DESCRIPTION:
Mapping XS 89537d94
END DESCRIPTION:
XS GIS Cut Line= 3
      1667160.74      6935674.95      1667258.46      6935945.44
      1667363.92      6936272.25
#Sta/Elev= 30
  4716.0 1809.50  4825.6 1809.09  4892.5 1808.13  4917.9 1807.48  4942.5 1806.36
  4973.9 1805.68  4985.1 1804.65  4999.5 1804.27  5000.0 1803.77  5004.7 1803.77
  5005.1 1804.27  5016.8 1805.08  5036.9 1807.98  5042.1 1809.03  5090.3 1811.74
  5106.2 1811.96  5111.5 1812.36  5121.9 1811.57  5132.4 1811.99  5138.3 1812.84
  5143.5 1813.12  5163.9 1813.52  5184.9 1814.46  5207.6 1814.86  5227.0 1815.71
  5239.6 1815.62  5266.4 1816.15  5271.7 1816.54  5321.5 1817.92  5347.0 1818.18
#Mann=3,-1,0
  4716.0   0.035       0  4999.5   0.035       0  5005.1   0.035       0
Bank Sta=4999.5,5005.1
Exp/Cntr=0.3,0.1

Type RM Length L Ch R = 1,10294,380,380,380
BEGIN DESCRIPTION:
Mapping XS 7ad7450a
END DESCRIPTION:
XS GIS Cut Line= 3
      1666764.08      6935412.05      1666784.53      6936057.62
      1666936.13      6936417.93
#Sta/Elev= 30
  4354.1 1813.19  4380.1 1812.00  4490.1 1808.98  4560.2 1807.83  4590.2 1807.84
  4600.2 1807.39  4630.2 1807.62  4730.2 1805.76  4856.2 1805.49  4917.5 1805.96
  4940.3 1806.13  4950.4 1805.45  4960.4 1803.91  4977.5 1802.79  4978.0 1802.29
  4982.7 1802.29  4983.2 1802.79  4997.7 1803.59  5015.4 1803.95  5098.1 1803.66
  5115.8 1803.59  5130.6 1804.05  5152.3 1805.49  5184.8 1806.36  5206.5 1807.75
  5216.2 1807.65  5239.1 1809.23  5245.3 1810.19  5274.5 1812.07  5390.9 1815.47
#Mann=5,-1,0
  4354.1   0.035       0  4917.5    0.07       0  4977.5    0.07       0
  4983.2    0.07       0  5098.1   0.035       0
Bank Sta=4977.5,4983.2
Exp/Cntr=0.3,0.1

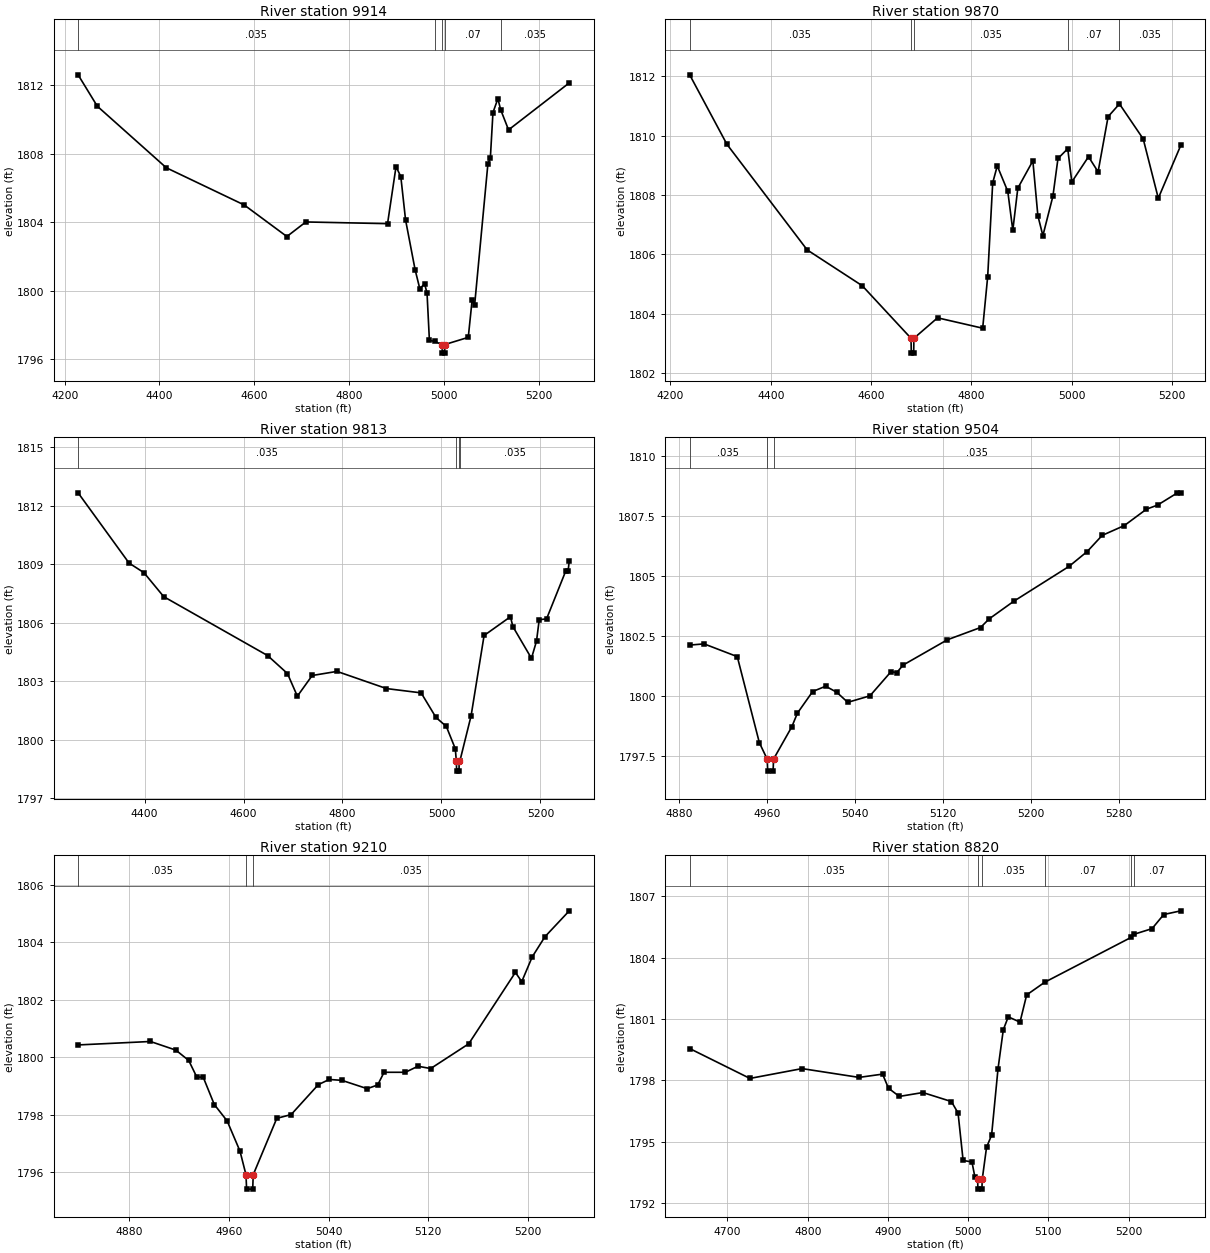
Type RM Length L Ch R = 1,9914,44,44,44
BEGIN DESCRIPTION:
Mapping XS 5b70d684
END DESCRIPTION:
XS GIS Cut Line= 5
      1666477.21      6935467.54      1666485.02      6935989.71
      1666492.83      6936117.32      1666503.25      6936242.32
      1666577.47      6936492.33
#Sta/Elev= 30
  4228.4 1812.59  4268.9 1810.76  4414.5 1807.17  4578.9 1805.00  4668.9 1803.16
  4708.9 1804.01  4881.3 1803.91  4899.2 1807.24  4909.3 1806.65  4919.3 1804.13
  4939.4 1801.23  4949.4 1800.11  4959.4 1800.41  4964.6 1799.86  4969.6 1797.11
  4980.8 1797.04  4996.4 1796.86  4996.8 1796.36  5001.6 1796.36  5002.1 1796.86
  5051.6 1797.28  5059.8 1799.47  5065.0 1799.16  5093.0 1807.39  5098.2 1807.74
  5103.7 1810.39  5114.1 1811.20  5119.9 1810.56  5136.6 1809.38  5264.7 1812.12
#Mann=5,-1,0
  4228.4   0.035       0  4980.8    0.07       0  4996.4    0.07       0
  5002.1    0.07       0  5119.9   0.035       0
Bank Sta=4996.4,5002.1
Exp/Cntr=0.3,0.1

Type RM Length L Ch R = 1,9870,57,57,57
BEGIN DESCRIPTION:
Mapping XS fce2248c
END DESCRIPTION:
XS GIS Cut Line= 4
      1666434.46      6935473.83      1666452.69      6936091.06
      1666459.20      6936238.19      1666465.71      6936453.02
#Sta/Elev= 30
  4238.3 1812.05  4312.5 1809.71  4472.6 1806.15  4582.6 1804.94  4679.8 1803.17
  4680.3 1802.67  4685.1 1802.67  4685.5 1803.17  4732.7 1803.86  4822.7 1803.51
  4832.7 1805.25  4842.7 1808.41  4851.8 1808.98  4872.8 1808.12  4882.8 1806.81
  4892.8 1808.23  4922.8 1809.15  4932.8 1807.30  4942.8 1806.63  4962.8 1807.96
  4972.9 1809.23  4992.4 1809.56  5000.5 1808.44  5033.8 1809.29  5052.9 1808.78
  5072.9 1810.64  5095.5 1811.07  5142.9 1809.89  5173.0 1807.89  5218.0 1809.68
#Mann=5,-1,0
  4238.3   0.035       0  4679.8    0.07       0  4685.5   0.035       0
  4992.4    0.07       0  5095.5   0.035       0
Bank Sta=4679.8,4685.5
Exp/Cntr=0.3,0.1

Type RM Length L Ch R = 1,9813,309,309,309
BEGIN DESCRIPTION:
Mapping XS 9680b52e
END DESCRIPTION:
XS GIS Cut Line= 4
      1666410.80      6935464.95      1666412.10      6936145.96
      1666414.71      6936204.56      1666369.15      6936453.15
#Sta/Elev= 30
  4265.8 1812.65  4368.8 1809.05  4398.8 1808.56  4438.8 1807.33  4648.8 1804.31
  4688.8 1803.39  4708.8 1802.23  4738.8 1803.29  4788.9 1803.50  4888.9 1802.62
  4958.9 1802.40  4988.9 1801.14  5009.8 1800.68  5027.9 1799.54  5030.1 1798.89
  5030.6 1798.39  5035.4 1798.39  5035.8 1798.89  5037.3 1798.92  5059.8 1801.22
  5086.1 1805.34  5139.3 1806.30  5144.4 1805.79  5181.8 1804.17  5192.0 1805.05
  5197.5 1806.15  5212.3 1806.19  5250.7 1808.62  5255.8 1808.63  5258.2 1809.17
#Mann=4,-1,0
  4265.8   0.035       0  5030.1   0.035       0  5035.8   0.035       0
  5037.3   0.035       0
Bank Sta=5030.1,5035.8
Exp/Cntr=0.3,0.1

Type RM Length L Ch R = 1,9504,294,294,294
BEGIN DESCRIPTION:
Mapping XS ed2dc428
END DESCRIPTION:
XS GIS Cut Line= 3
      1666140.25      6936024.94      1666151.77      6936139.63
      1666189.54      6936469.10
#Sta/Elev= 30
  4889.7 1802.12  4902.8 1802.17  4933.0 1801.64  4953.1 1798.06  4960.2 1797.38
  4960.7 1796.88  4965.6 1796.88  4966.0 1797.38  4982.7 1798.73  4987.7 1799.29
  5001.6 1800.19  5013.4 1800.41  5023.5 1800.16  5033.5 1799.74  5053.7 1800.01
  5073.0 1801.02  5078.0 1800.97  5083.9 1801.29  5124.1 1802.34  5154.3 1802.85
  5162.2 1803.21  5184.5 1803.94  5234.8 1805.39  5251.4 1806.01  5265.0 1806.68
  5285.2 1807.09  5305.3 1807.77  5315.4 1807.94  5333.5 1808.45  5336.6 1808.45
#Mann=3,-1,0
  4889.7   0.035       0  4960.2   0.035       0  4966.0   0.035       0
Bank Sta=4960.2,4966
Exp/Cntr=0.3,0.1

Type RM Length L Ch R = 1,9210,390,390,390
BEGIN DESCRIPTION:
Mapping XS 7239ffec
END DESCRIPTION:
XS GIS Cut Line= 3
      1665857.83      6936081.68      1665895.26      6936240.39
      1665937.59      6936467.21
#Sta/Elev= 30
  4839.2 1800.43  4897.2 1800.55  4917.6 1800.25  4927.9 1799.89  4934.4 1799.31
  4939.5 1799.31  4948.4 1798.36  4958.7 1797.79  4969.0 1796.74  4973.8 1795.92
  4974.3 1795.42  4979.2 1795.42  4979.6 1795.92  4998.5 1797.88  5010.0 1798.01
  5031.8 1799.05  5040.5 1799.23  5050.7 1799.20  5071.0 1798.91  5079.4 1799.04
  5084.5 1799.48  5101.6 1799.48  5111.7 1799.69  5121.9 1799.61  5152.4 1800.47
  5189.8 1802.95  5194.9 1802.63  5203.3 1803.49  5213.5 1804.19  5233.0 1805.09
#Mann=3,-1,0
  4839.2   0.035       0  4973.8   0.035       0  4979.6   0.035       0
Bank Sta=4973.8,4979.6
Exp/Cntr=0.3,0.1

Type RM Length L Ch R = 1,8820,1040,1040,1040
BEGIN DESCRIPTION:
Mapping XS ec457115
END DESCRIPTION:
XS GIS Cut Line= 3
      1665740.89      6936057.73      1665533.65      6936342.00
      1665377.41      6936550.33
#Sta/Elev= 30
  4652.9 1799.56  4728.0 1798.10  4792.9 1798.58  4864.0 1798.15  4893.3 1798.31
  4900.7 1797.62  4914.2 1797.22  4943.5 1797.41  4979.1 1796.97  4987.4 1796.41
  4993.7 1794.09  5004.7 1794.02  5008.4 1793.28  5011.7 1793.19  5012.2 1792.69
  5017.1 1792.69  5017.6 1793.19  5022.9 1794.73  5029.2 1795.33  5037.2 1798.57
  5043.8 1800.48  5050.0 1801.11  5064.6 1800.85  5072.9 1802.18  5095.4 1802.80
  5203.0 1804.99  5206.4 1805.14  5229.2 1805.42  5243.8 1806.11  5265.1 1806.29
#Mann=6,-1,0
  4652.9   0.035       0  5011.7   0.035       0  5017.6   0.035       0
  5095.4    0.07       0  5203.0   0.035       0  5206.4    0.07       0
Bank Sta=5011.7,5017.6
Exp/Cntr=0.3,0.1

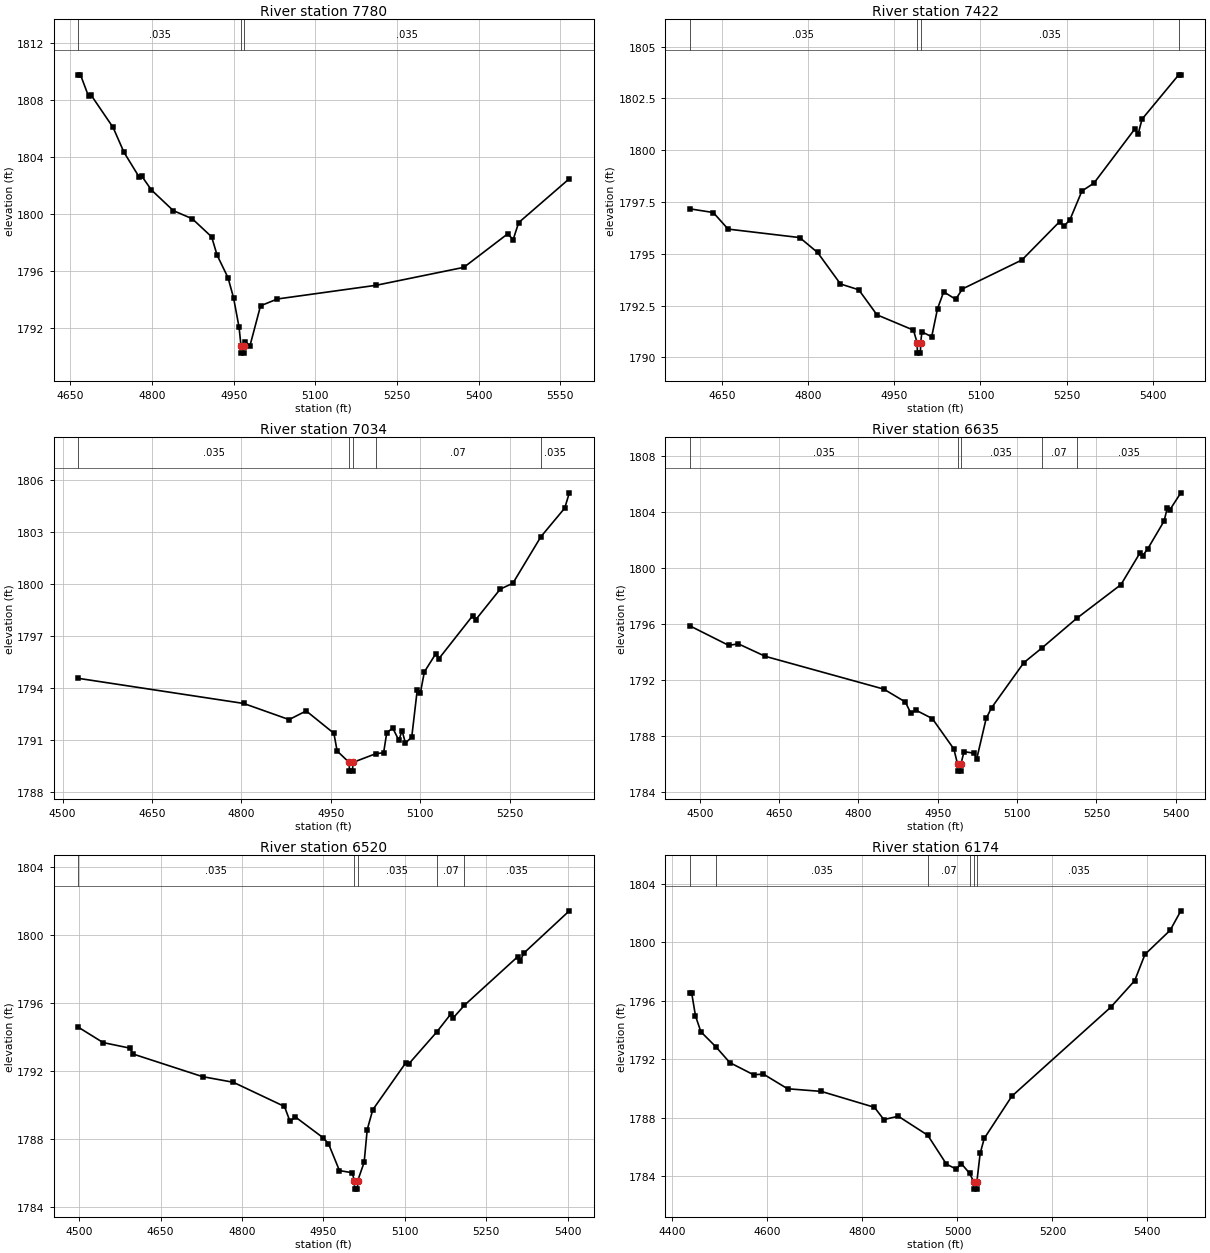
Type RM Length L Ch R = 1,7780,358,358,358
BEGIN DESCRIPTION:
Mapping XS f36b8e6a
END DESCRIPTION:
XS GIS Cut Line= 3
      1665077.93      6935604.20      1665113.73      6935941.61
      1665179.92      6936500.40
#Sta/Elev= 30
  4664.4 1809.74  4668.8 1809.74  4683.7 1808.22  4688.7 1808.29  4728.6 1806.05
  4748.7 1804.30  4776.3 1802.58  4781.3 1802.63  4799.0 1801.66  4839.2 1800.21
  4874.0 1799.64  4909.6 1798.37  4919.6 1797.09  4939.7 1795.50  4949.8 1794.10
  4959.9 1792.04  4963.6 1790.71  4964.1 1790.21  4969.2 1790.21  4969.7 1790.71
  4971.6 1790.98  4980.0 1790.73  4999.4 1793.53  5030.3 1794.01  5211.5 1794.97
  5372.7 1796.23  5453.2 1798.58  5463.3 1798.18  5473.4 1799.37  5566.4 1802.45
#Mann=3,-1,0
  4664.4   0.035       0  4963.6   0.035       0  4969.7   0.035       0
Bank Sta=4963.6,4969.7
Exp/Cntr=0.3,0.1

Type RM Length L Ch R = 1,7422,388,388,388
BEGIN DESCRIPTION:
Mapping XS d6b2ca80
END DESCRIPTION:
XS GIS Cut Line= 3
      1664797.97      6935780.05      1664932.09      6936166.80
      1665062.30      6936592.59
#Sta/Elev= 30
  4594.0 1797.17  4635.1 1796.99  4660.9 1796.19  4785.5 1795.78  4816.6 1795.06
  4856.4 1793.54  4888.2 1793.26  4919.9 1792.05  4983.4 1791.31  4989.8 1790.70
  4990.3 1790.20  4995.5 1790.20  4996.0 1790.70  4998.1 1791.23  5015.1 1790.99
  5025.3 1792.35  5036.0 1793.16  5056.9 1792.80  5068.6 1793.30  5172.2 1794.70
  5237.7 1796.55  5245.1 1796.33  5255.6 1796.64  5276.5 1798.03  5297.4 1798.41
  5368.9 1801.04  5374.1 1800.76  5381.1 1801.50  5444.9 1803.64  5448.6 1803.64
#Mann=4,-1,0
  4594.0   0.035       0  4989.8   0.035       0  4996.0   0.035       0
  5444.9    0.07       0
Bank Sta=4989.8,4996
Exp/Cntr=0.3,0.1

Type RM Length L Ch R = 1,7034,399,399,399
BEGIN DESCRIPTION:
Mapping XS ba0d860f
END DESCRIPTION:
XS GIS Cut Line= 3
      1664493.72      6935874.27      1664687.73      6936309.16
      1664803.62      6936637.29
#Sta/Elev= 30
  4525.9 1794.57  4803.7 1793.12  4879.9 1792.19  4908.6 1792.69  4955.1 1791.40
  4960.5 1790.38  4980.7 1789.72  4981.2 1789.22  4986.4 1789.22  4986.9 1789.72
  5025.0 1790.22  5038.5 1790.28  5043.8 1791.44  5053.9 1791.70  5064.1 1790.99
  5069.4 1791.56  5075.1 1790.84  5085.7 1791.18  5095.0 1793.92  5100.3 1793.75
  5106.9 1794.94  5125.9 1795.98  5131.2 1795.70  5187.8 1798.17  5193.1 1797.95
  5234.2 1799.71  5255.4 1800.05  5302.4 1802.73  5342.4 1804.38  5350.1 1805.26
#Mann=5,-1,0
  4525.9   0.035       0  4980.7   0.035       0  4986.9   0.035       0
  5025.0    0.07       0  5302.4   0.035       0
Bank Sta=4980.7,4986.9
Exp/Cntr=0.3,0.1

Type RM Length L Ch R = 1,6635,115,115,115
BEGIN DESCRIPTION:
Mapping XS a6add84f
END DESCRIPTION:
XS GIS Cut Line= 3
      1664423.63      6935747.71      1664323.37      6936260.75
      1664245.24      6936659.22
#Sta/Elev= 30
  4480.8 1795.88  4554.7 1794.48  4572.8 1794.59  4623.7 1793.70  4847.9 1791.36
  4888.7 1790.44  4898.9 1789.65  4909.0 1789.85  4939.6 1789.26  4980.4 1787.09
  4987.4 1786.01  4987.9 1785.51  4993.2 1785.51  4993.7 1786.01  4999.6 1786.90
  5018.5 1786.79  5023.6 1786.38  5041.5 1789.27  5051.7 1790.03  5112.8 1793.25
  5146.8 1794.29  5212.4 1796.40  5296.3 1798.81  5332.4 1801.08  5337.5 1800.88
  5347.2 1801.38  5377.8 1803.34  5383.9 1804.27  5389.0 1804.16  5409.6 1805.36
#Mann=5,-1,0
  4480.8   0.035       0  4987.4   0.035       0  4993.7   0.035       0
  5146.8    0.07       0  5212.4   0.035       0
Bank Sta=4987.4,4993.7
Exp/Cntr=0.3,0.1

Type RM Length L Ch R = 1,6520,346,346,346
BEGIN DESCRIPTION:
Mapping XS ad04f543
END DESCRIPTION:
XS GIS Cut Line= 3
      1664296.02      6935742.54      1664215.29      6936241.21
      1664117.63      6936629.25
#Sta/Elev= 30
  4497.9 1794.58  4543.9 1793.67  4593.8 1793.34  4598.9 1793.00  4727.3 1791.67
  4783.9 1791.34  4878.2 1789.92  4888.4 1789.05  4898.5 1789.30  4949.2 1788.09
  4959.3 1787.74  4979.5 1786.16  5003.1 1786.03  5006.9 1785.57  5007.4 1785.07
  5012.8 1785.07  5013.3 1785.57  5025.1 1786.65  5030.7 1788.56  5041.0 1789.73
  5102.2 1792.50  5107.4 1792.42  5158.6 1794.28  5184.4 1795.33  5189.6 1795.13
  5209.9 1795.86  5307.8 1798.70  5312.9 1798.47  5319.4 1798.92  5403.2 1801.40
#Mann=5,-1,0
  4497.9   0.035       0  5006.9   0.035       0  5013.3   0.035       0
  5158.6    0.07       0  5209.9   0.035       0
Bank Sta=5006.9,5013.3
Exp/Cntr=0.3,0.1

Type RM Length L Ch R = 1,6174,334,334,334
BEGIN DESCRIPTION:
Mapping XS a1820ad4
END DESCRIPTION:
XS GIS Cut Line= 3
      1663992.63      6935584.57      1663900.19      6936144.43
      1663815.65      6936603.57
#Sta/Elev= 30
  4436.1 1796.54  4440.4 1796.54  4448.4 1794.97  4459.8 1793.88  4492.3 1792.82
  4520.7 1791.77  4570.6 1790.94  4591.6 1790.98  4642.3 1789.98  4713.2 1789.80
  4825.2 1788.71  4845.0 1787.87  4875.4 1788.10  4937.4 1786.80  4976.8 1784.82
  4997.0 1784.49  5008.4 1784.85  5025.4 1784.20  5034.4 1783.61  5034.9 1783.11
  5040.4 1783.11  5040.9 1783.61  5047.8 1785.55  5056.4 1786.58  5114.5 1789.47
  5322.4 1795.55  5373.2 1797.38  5394.9 1799.18  5447.9 1800.83  5470.4 1802.16
#Mann=6,-1,0
  4436.1    0.07       0  4492.3   0.035       0  4937.4    0.07       0
  5025.4   0.035       0  5034.4    0.07       0  5040.9   0.035       0
Bank Sta=5034.4,5040.9
Exp/Cntr=0.3,0.1