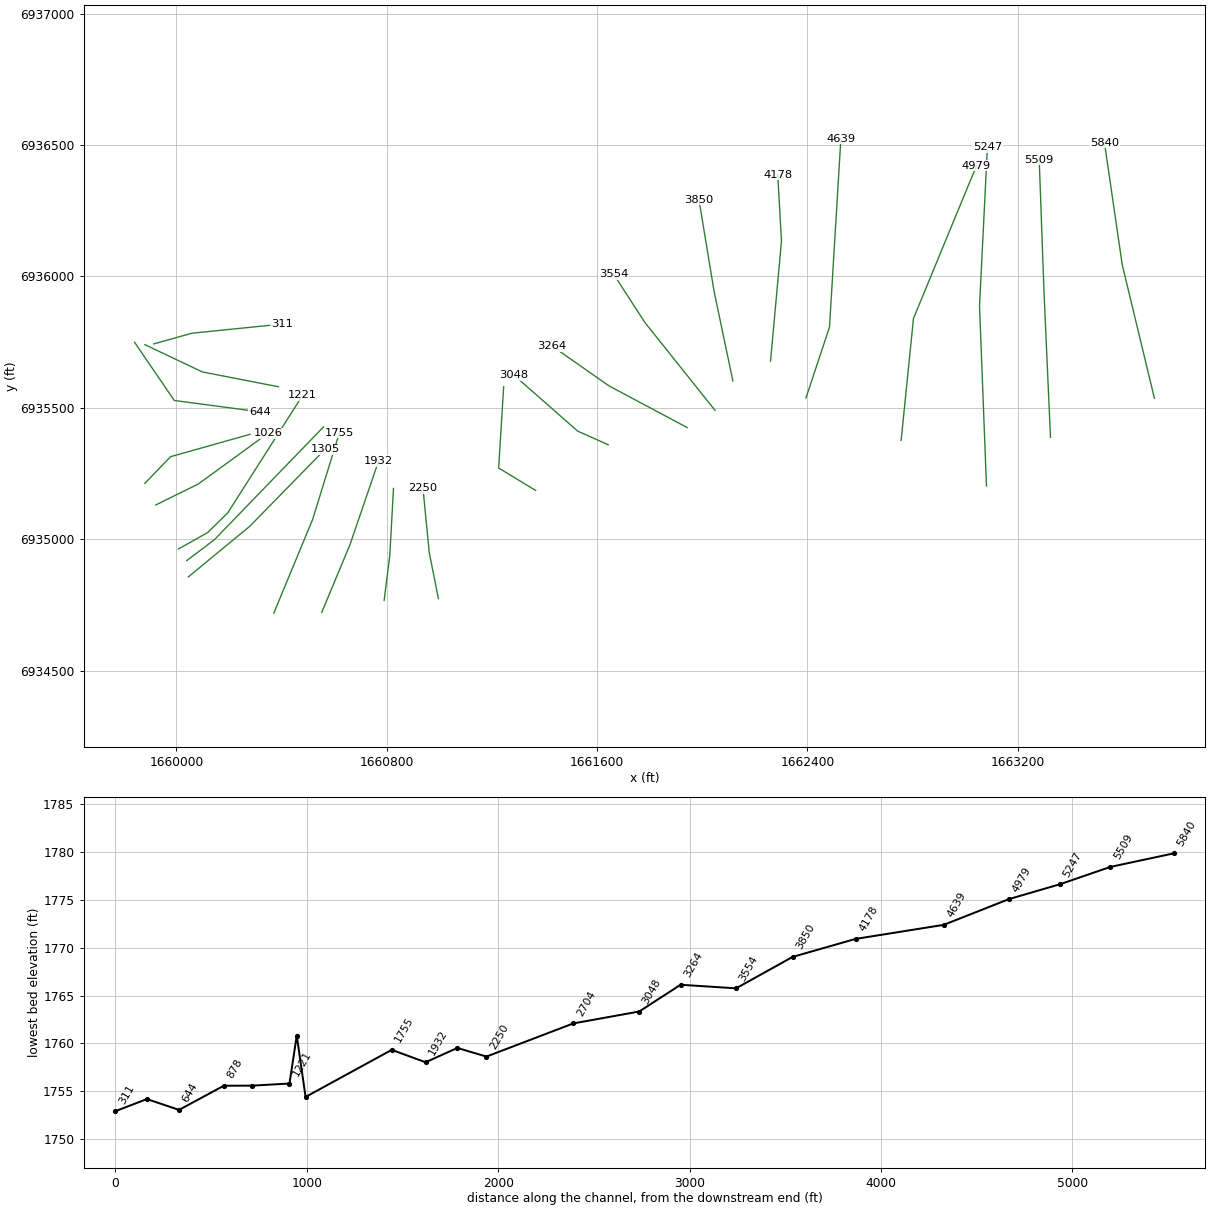
HEC-RAS study Chimney Creek 1099.prj: Chimney Creek 1099 Base Level Engineering

--- Chimney Creek 1099.g01 (geometry) --- (continued)

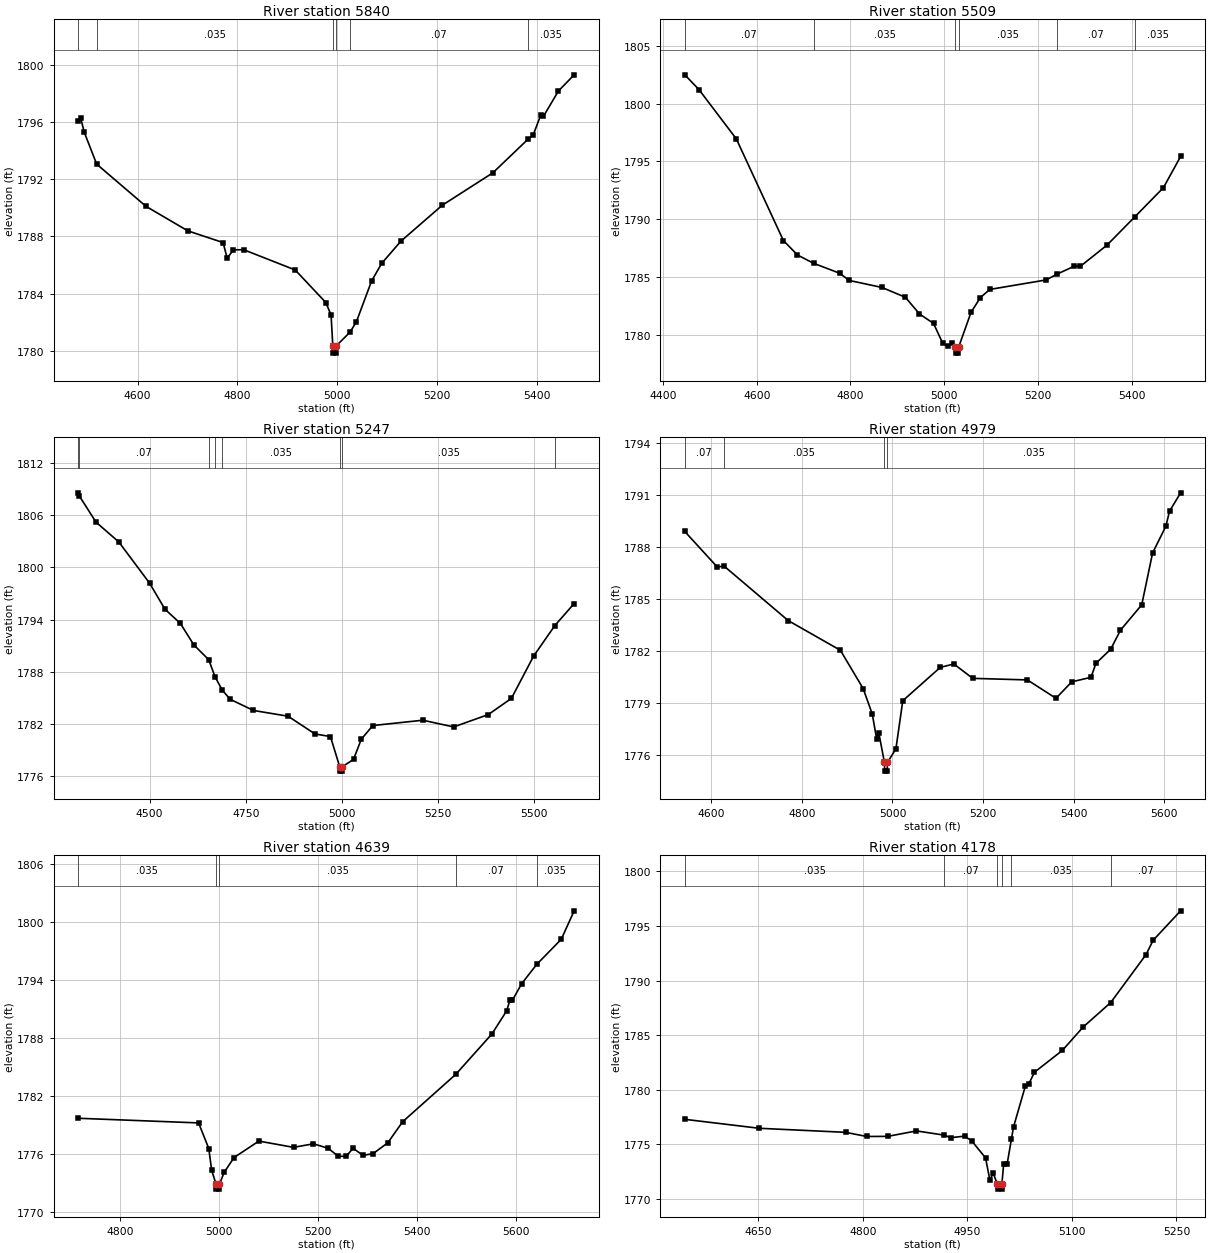
Type RM Length L Ch R = 1,5840,331,331,331
BEGIN DESCRIPTION:
Mapping XS 7a47d1a8
END DESCRIPTION:
XS GIS Cut Line= 3
      1663720.49      6935536.39      1663598.11      6936044.17
      1663530.39      6936509.04
#Sta/Elev= 30
  4481.6 1796.12  4486.1 1796.32  4493.5 1795.30  4518.3 1793.07  4617.0 1790.11
  4700.8 1788.39  4771.3 1787.57  4779.4 1786.47  4791.9 1787.06  4812.4 1787.07
  4915.5 1785.65  4977.0 1783.36  4987.3 1782.49  4990.8 1780.32  4991.3 1779.82
  4996.9 1779.82  4997.4 1780.32  5025.5 1781.30  5038.1 1782.03  5068.4 1784.88
  5088.6 1786.11  5126.8 1787.66  5209.9 1790.19  5311.0 1792.46  5380.9 1794.80
  5391.8 1795.12  5407.0 1796.52  5412.1 1796.41  5442.3 1798.20  5473.7 1799.33
#Mann=6,-1,0
  4481.6    0.07       0  4518.3   0.035       0  4990.8   0.035       0
  4997.4   0.035       0  5025.5    0.07       0  5380.9   0.035       0
Bank Sta=4990.8,4997.4
Exp/Cntr=0.3,0.1

Type RM Length L Ch R = 1,5509,262,262,262
BEGIN DESCRIPTION:
Mapping XS ab9747ba
END DESCRIPTION:
XS GIS Cut Line= 3
      1663325.10      6935387.90      1663300.36      6935942.60
      1663282.20      6936444.72
#Sta/Elev= 30
  4446.6 1802.48  4476.7 1801.21  4556.5 1796.94  4656.9 1788.15  4686.9 1786.90
  4721.3 1786.18  4777.0 1785.32  4797.0 1784.70  4867.1 1784.09  4917.2 1783.24
  4947.2 1781.80  4977.2 1780.98  4997.0 1779.25  5007.1 1779.02  5017.3 1779.31
  5024.0 1778.91  5024.5 1778.41  5030.1 1778.41  5030.6 1778.91  5057.3 1781.95
  5077.3 1783.22  5097.3 1783.92  5217.4 1784.74  5240.1 1785.23  5277.4 1785.93
  5290.5 1785.92  5347.5 1787.76  5406.4 1790.19  5467.6 1792.72  5504.3 1795.42
#Mann=6,-1,0
  4446.6    0.07       0  4721.3   0.035       0  5024.0   0.035       0
  5030.6   0.035       0  5240.1    0.07       0  5406.4   0.035       0
Bank Sta=5024,5030.6
Exp/Cntr=0.3,0.1

Type RM Length L Ch R = 1,5247,268,268,268
BEGIN DESCRIPTION:
Mapping XS 37b204b2
END DESCRIPTION:
XS GIS Cut Line= 3
      1663081.61      6935202.98      1663055.14      6935887.67
      1663085.09      6936490.92
#Sta/Elev= 30
  4314.8 1808.54  4317.7 1808.16  4360.7 1805.18  4419.9 1802.91  4500.0 1798.18
  4540.0 1795.19  4580.0 1793.56  4615.2 1791.09  4653.9 1789.39  4670.2 1787.44
  4689.3 1785.88  4710.1 1784.84  4770.2 1783.57  4860.2 1782.91  4930.3 1780.87
  4970.3 1780.58  4994.4 1777.11  4994.9 1776.61  5000.5 1776.61  5001.0 1777.11
  5030.4 1777.96  5050.4 1780.26  5080.4 1781.84  5210.6 1782.45  5290.7 1781.68
  5380.8 1783.10  5440.9 1784.96  5498.6 1789.81  5553.8 1793.31  5604.0 1795.84
#Mann=8,-1,0
  4314.8   0.035       0  4317.7    0.07       0  4653.9   0.035       0
  4670.2    0.07       0  4689.3   0.035       0  4994.4   0.035       0
  5001.0   0.035       0  5553.8    0.07       0
Bank Sta=4994.4,5001
Exp/Cntr=0.3,0.1

Type RM Length L Ch R = 1,4979,340,340,340
BEGIN DESCRIPTION:
Mapping XS 26027837
END DESCRIPTION:
XS GIS Cut Line= 3
      1662756.97      6935376.41      1662803.85      6935839.92
      1663043.44      6936420.67
#Sta/Elev= 30
  4541.7 1788.87  4613.7 1786.81  4627.7 1786.89  4770.0 1783.73  4885.0 1782.02
  4935.3 1779.81  4955.4 1778.34  4964.9 1776.93  4969.9 1777.24  4982.2 1775.55
  4982.7 1775.05  4988.4 1775.05  4988.9 1775.55  5007.6 1776.34  5022.7 1779.11
  5105.3 1781.03  5135.3 1781.23  5177.1 1780.40  5297.6 1780.31  5360.8 1779.25
  5395.6 1780.20  5438.0 1780.46  5449.0 1781.27  5481.5 1782.08  5503.1 1783.18
  5550.0 1784.64  5573.9 1787.63  5603.2 1789.17  5611.3 1790.04  5635.8 1791.10
#Mann=4,-1,0
  4541.7    0.07       0  4627.7   0.035       0  4982.2   0.035       0
  4988.9   0.035       0
Bank Sta=4982.2,4988.9
Exp/Cntr=0.3,0.1

Type RM Length L Ch R = 1,4639,461,461,461
BEGIN DESCRIPTION:
Mapping XS 7cddd4d6
END DESCRIPTION:
XS GIS Cut Line= 3
      1662394.98      6935537.80      1662484.45      6935807.44
      1662527.75      6936523.94
#Sta/Elev= 30
  4715.9 1779.70  4958.9 1779.22  4979.5 1776.57  4985.3 1774.32  4994.3 1772.87
  4994.8 1772.37  5000.5 1772.37  5001.0 1772.87  5010.6 1774.11  5030.6 1775.64
  5080.7 1777.34  5150.8 1776.69  5190.9 1777.06  5221.0 1776.59  5241.0 1775.77
  5256.9 1775.76  5271.1 1776.59  5291.1 1775.87  5311.1 1776.03  5341.2 1777.16
  5371.2 1779.34  5478.5 1784.24  5551.6 1788.42  5581.6 1790.83  5588.0 1791.94
  5593.0 1791.91  5611.7 1793.62  5642.0 1795.61  5691.8 1798.22  5717.8 1801.16
#Mann=5,-1,0
  4715.9   0.035       0  4994.3   0.035       0  5001.0   0.035       0
  5478.5    0.07       0  5642.0   0.035       0
Bank Sta=4994.3,5001
Exp/Cntr=0.3,0.1

Type RM Length L Ch R = 1,4178,328,328,328
BEGIN DESCRIPTION:
Mapping XS fceb04d1
END DESCRIPTION:
XS GIS Cut Line= 3
      1662260.15      6935677.94      1662301.81      6936134.94
      1662287.49      6936387.53
#Sta/Elev= 30
  4544.2 1777.29  4651.2 1776.47  4775.2 1776.10  4805.3 1775.72  4835.5 1775.73
  4876.8 1776.23  4917.0 1775.84  4925.8 1775.61  4945.9 1775.75  4956.0 1775.33
  4976.0 1773.76  4982.1 1771.76  4987.1 1772.34  4992.7 1771.40  4993.2 1770.90
  4999.0 1770.90  4999.5 1771.40  5002.1 1773.23  5007.1 1773.23  5013.2 1775.49
  5016.2 1776.60  5033.1 1780.32  5038.1 1780.53  5046.2 1781.60  5086.3 1783.60
  5116.3 1785.75  5155.7 1787.98  5206.5 1792.38  5216.6 1793.68  5256.1 1796.38
#Mann=6,-1,0
  4544.2   0.035       0  4917.0    0.07       0  4992.7    0.07       0
  4999.5    0.07       0  5013.2   0.035       0  5155.7    0.07       0
Bank Sta=4992.7,4999.5
Exp/Cntr=0.3,0.1

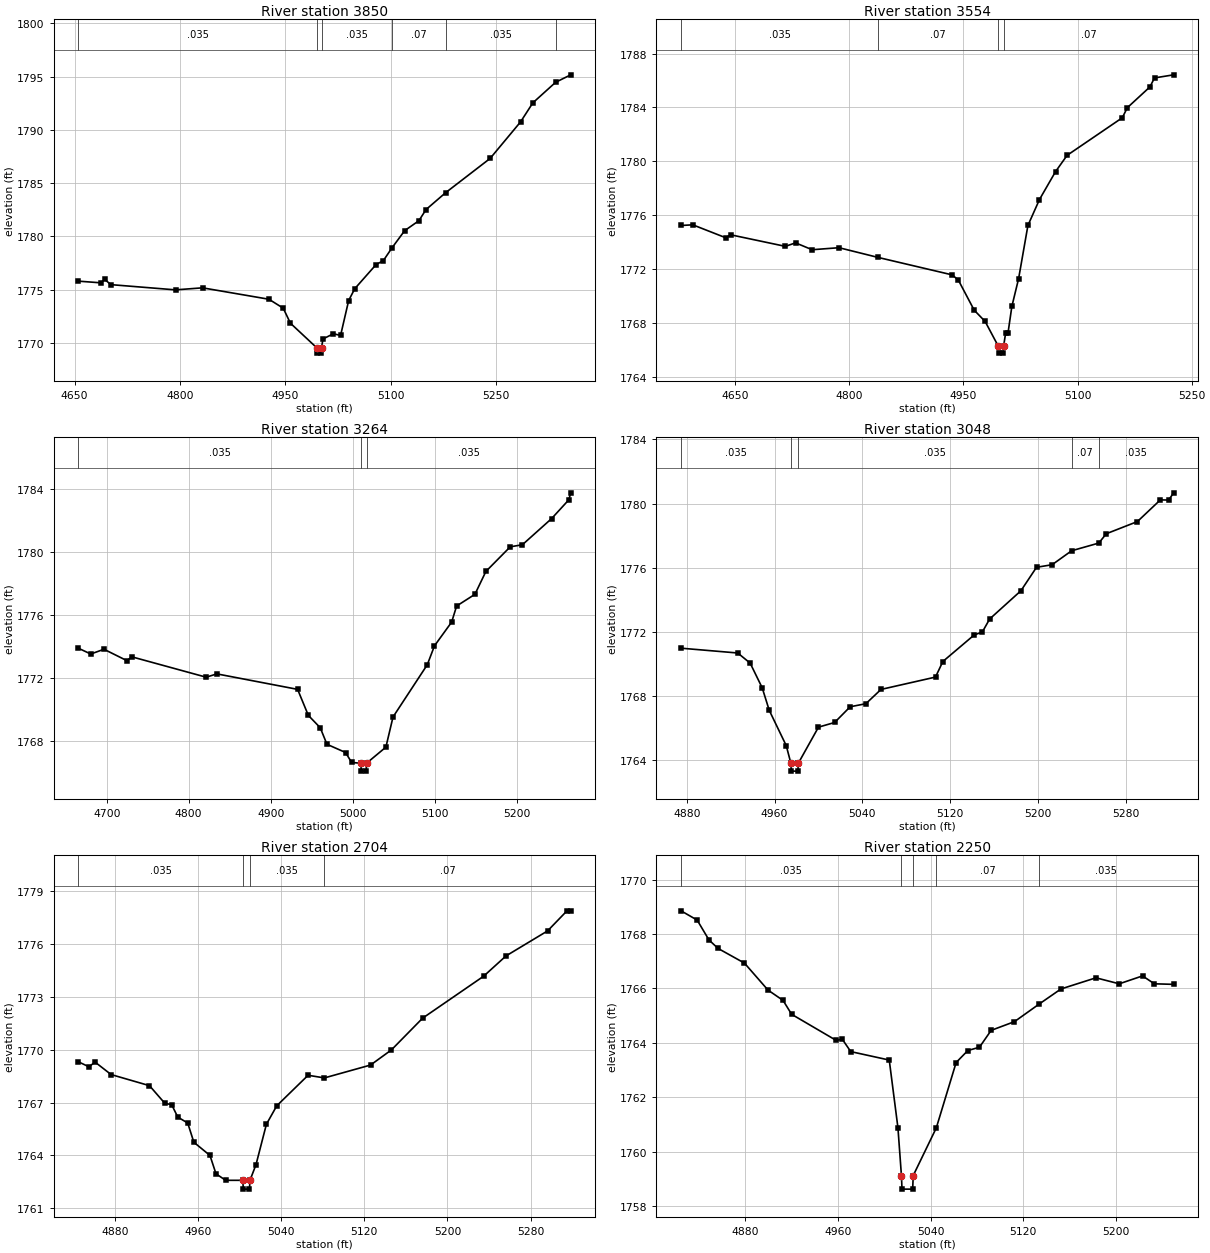
Type RM Length L Ch R = 1,3850,296,296,296
BEGIN DESCRIPTION:
Mapping XS 13a19e49
END DESCRIPTION:
XS GIS Cut Line= 3
      1662116.91      6935602.41      1662045.30      6935943.53
      1661988.01      6936291.18
#Sta/Elev= 30
  4655.2 1775.79  4687.6 1775.63  4692.8 1775.96  4701.8 1775.46  4793.7 1774.97
  4832.2 1775.16  4926.6 1774.09  4947.0 1773.25  4957.2 1771.84  4994.7 1769.53
  4995.2 1769.03  5001.0 1769.03  5001.5 1769.53  5003.5 1770.36  5018.4 1770.85
  5028.6 1770.69  5040.1 1773.97  5048.8 1775.08  5079.2 1777.35  5089.4 1777.71
  5101.6 1778.90  5119.8 1780.53  5140.0 1781.46  5150.2 1782.51  5178.0 1784.09
  5241.4 1787.31  5284.7 1790.74  5302.2 1792.53  5334.6 1794.46  5356.1 1795.16
#Mann=6,-1,0
  4655.2   0.035       0  4994.7   0.035       0  5001.5   0.035       0
  5101.6    0.07       0  5178.0   0.035       0  5334.6    0.07       0
Bank Sta=4994.7,5001.5
Exp/Cntr=0.3,0.1

Type RM Length L Ch R = 1,3554,290,290,290
BEGIN DESCRIPTION:
Mapping XS e151d41b
END DESCRIPTION:
XS GIS Cut Line= 3
      1662049.21      6935490.40      1661782.28      6935824.61
      1661662.94      6936009.04
#Sta/Elev= 30
  4578.8 1775.23  4594.2 1775.28  4637.5 1774.32  4643.9 1774.54  4715.9 1773.68
  4729.3 1773.94  4751.1 1773.43  4786.4 1773.58  4837.6 1772.86  4935.3 1771.56
  4943.3 1771.17  4964.1 1768.94  4978.5 1768.10  4995.9 1766.25  4996.4 1765.75
  5002.2 1765.75  5002.7 1766.25  5005.5 1767.27  5008.6 1767.27  5013.6 1769.22
  5022.5 1771.29  5034.7 1775.23  5049.9 1777.16  5071.0 1779.23  5086.2 1780.44
  5158.7 1783.23  5165.4 1783.98  5195.0 1785.52  5201.1 1786.19  5226.2 1786.42
#Mann=4,-1,0
  4578.8   0.035       0  4837.6    0.07       0  4995.9    0.07       0
  5002.7    0.07       0
Bank Sta=4995.9,5002.7
Exp/Cntr=0.3,0.1

Type RM Length L Ch R = 1,3264,216,216,216
BEGIN DESCRIPTION:
Mapping XS 45a1ad69
END DESCRIPTION:
XS GIS Cut Line= 3
      1661942.84      6935425.32      1661645.56      6935583.72
      1661429.24      6935735.14
#Sta/Elev= 30
  4665.2 1773.91  4680.6 1773.54  4696.7 1773.84  4724.6 1773.12  4730.7 1773.36
  4821.4 1772.07  4834.4 1772.28  4932.9 1771.30  4946.0 1769.65  4960.5 1768.87
  4968.7 1767.82  4991.4 1767.30  4998.8 1766.67  5010.1 1766.62  5010.6 1766.12
  5016.5 1766.12  5017.0 1766.62  5040.6 1767.64  5049.3 1769.55  5091.1 1772.86
  5099.9 1774.06  5120.8 1775.56  5126.9 1776.58  5149.2 1777.32  5162.6 1778.77
  5192.3 1780.33  5207.1 1780.46  5242.8 1782.12  5263.8 1783.31  5266.1 1783.75
#Mann=3,-1,0
  4665.2   0.035       0  5010.1   0.035       0  5017.0   0.035       0
Bank Sta=5010.1,5017
Exp/Cntr=0.3,0.1

Type RM Length L Ch R = 1,3048,344,344,344
BEGIN DESCRIPTION:
Mapping XS 66eaa435
END DESCRIPTION:
XS GIS Cut Line= 3
      1661642.50      6935359.77      1661526.20      6935411.85
      1661284.54      6935624.16
#Sta/Elev= 30
  4874.7 1770.99  4926.4 1770.69  4937.7 1770.06  4948.7 1768.52  4955.1 1767.12
  4970.6 1764.92  4974.8 1763.83  4975.3 1763.33  4981.2 1763.33  4981.7 1763.83
  5000.0 1766.07  5014.7 1766.36  5028.9 1767.34  5043.2 1767.53  5057.0 1768.42
  5106.7 1769.19  5113.4 1770.16  5141.9 1771.81  5149.4 1772.00  5156.1 1772.81
  5184.6 1774.57  5198.8 1776.03  5213.0 1776.19  5230.8 1777.06  5255.6 1777.54
  5262.4 1778.12  5290.8 1778.88  5311.7 1780.23  5319.3 1780.22  5323.8 1780.67
#Mann=5,-1,0
  4874.7   0.035       0  4974.8   0.035       0  4981.7   0.035       0
  5230.8    0.07       0  5255.6   0.035       0
Bank Sta=4974.8,4981.7
Exp/Cntr=0.3,0.1

Type RM Length L Ch R = 1,2704,454,454,454
BEGIN DESCRIPTION:
Mapping XS 6bff8109
END DESCRIPTION:
XS GIS Cut Line= 3
      1661366.44      6935186.17      1661225.86      6935271.22
      1661244.95      6935580.22
#Sta/Elev= 30
  4844.7 1769.32  4855.1 1769.03  4860.9 1769.30  4876.4 1768.59  4913.3 1767.96
  4928.2 1766.95  4934.6 1766.89  4940.5 1766.18  4950.1 1765.84  4956.0 1764.75
  4971.5 1764.00  4977.3 1762.96  4986.6 1762.59  5003.1 1762.59  5003.6 1762.09
  5009.5 1762.09  5010.0 1762.59  5015.8 1763.48  5025.8 1765.77  5035.8 1766.82
  5065.9 1768.55  5081.6 1768.40  5126.0 1769.13  5146.1 1769.99  5176.1 1771.79
  5234.8 1774.17  5256.3 1775.32  5296.3 1776.74  5315.0 1777.88  5318.6 1777.88
#Mann=4,-1,0
  4844.7   0.035       0  5003.1   0.035       0  5010.0   0.035       0
  5081.6    0.07       0
Bank Sta=5003.1,5010
Exp/Cntr=0.3,0.1

Type RM Length L Ch R = 1,2250,152,152,152
BEGIN DESCRIPTION:
Mapping XS 25350051
END DESCRIPTION:
XS GIS Cut Line= 3
      1660996.79      6934774.41      1660962.06      6934948.02
      1660937.92      6935194.69
#Sta/Elev= 30
  4824.8 1768.85  4838.7 1768.51  4848.9 1767.78  4856.7 1767.47  4879.5 1766.93
  4899.8 1765.94  4912.8 1765.56  4920.2 1765.05  4958.7 1764.09  4963.8 1764.14
  4971.2 1763.68  5004.4 1763.37  5011.9 1760.88  5014.9 1759.13  5015.4 1758.63
  5024.6 1758.63  5025.1 1759.13  5045.0 1760.88  5062.1 1763.28  5072.2 1763.72
  5082.2 1763.84  5092.3 1764.46  5112.4 1764.78  5133.5 1765.42  5152.5 1765.98
  5182.7 1766.39  5202.8 1766.17  5222.9 1766.46  5233.1 1766.17  5249.7 1766.15
#Mann=5,-1,0
  4824.8   0.035       0  5014.9   0.035       0  5025.1   0.035       0
  5045.0    0.07       0  5133.5   0.035       0
Bank Sta=5014.9,5025.1
Exp/Cntr=0.3,0.1

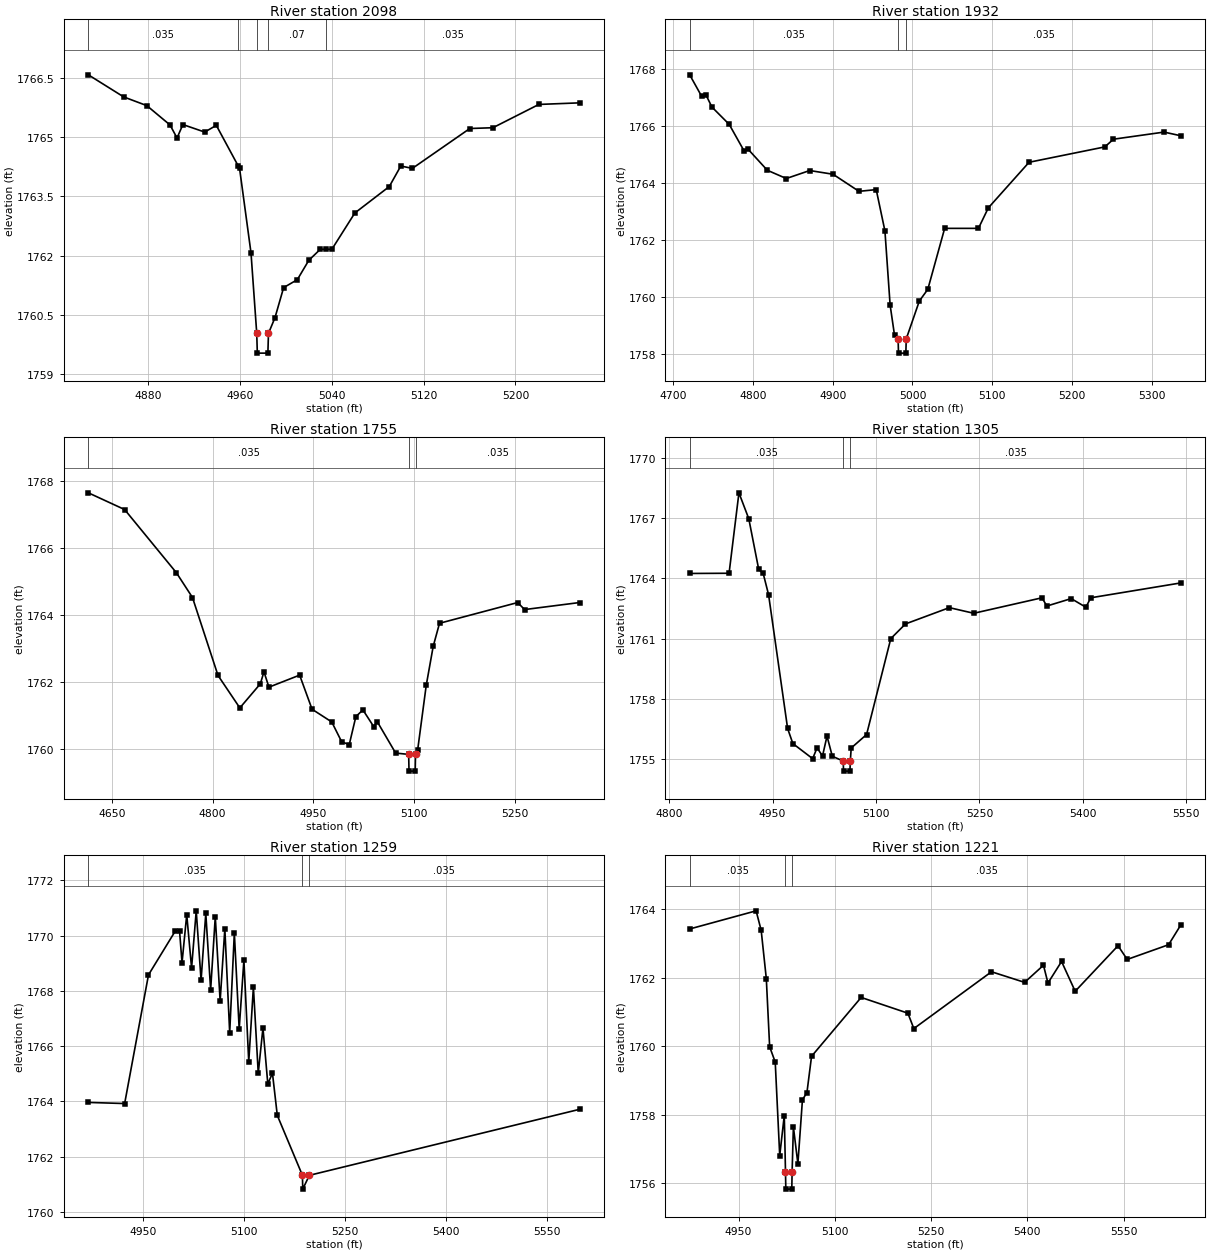
Type RM Length L Ch R = 1,2098,166,166,166
BEGIN DESCRIPTION:
Mapping XS ad2b2ee3
END DESCRIPTION:
XS GIS Cut Line= 3
      1660790.19      6934767.47      1660811.89      6934939.34
      1660825.76      6935193.33
#Sta/Elev= 30
  4828.2 1766.58  4859.0 1766.02  4879.1 1765.80  4899.3 1765.31  4905.4 1764.98
  4910.5 1765.32  4929.5 1765.13  4939.6 1765.30  4958.7 1764.27  4959.8 1764.22
  4969.8 1762.07  4974.8 1760.03  4975.3 1759.53  4984.5 1759.53  4985.0 1760.03
  4990.7 1760.43  4998.2 1761.19  5010.1 1761.39  5020.1 1761.88  5030.1 1762.16
  5034.8 1762.16  5040.2 1762.16  5060.2 1763.08  5090.2 1763.75  5100.2 1764.27
  5110.3 1764.21  5160.3 1765.22  5180.4 1765.24  5220.4 1765.83  5255.8 1765.87
#Mann=5,-1,0
  4828.2   0.035       0  4958.7    0.07       0  4974.8    0.07       0
  4985.0    0.07       0  5034.8   0.035       0
Bank Sta=4974.8,4985
Exp/Cntr=0.3,0.1

Type RM Length L Ch R = 1,1932,177,177,177
BEGIN DESCRIPTION:
Mapping XS d600df1a
END DESCRIPTION:
XS GIS Cut Line= 3
      1660553.01      6934722.35      1660660.55      6934980.49
      1660769.15      6935297.88
#Sta/Elev= 30
  4721.0 1767.81  4735.9 1767.06  4741.3 1767.11  4748.8 1766.68  4770.5 1766.07
  4788.9 1765.15  4794.4 1765.19  4818.2 1764.46  4842.0 1764.17  4871.3 1764.45
  4900.5 1764.32  4933.0 1763.72  4954.6 1763.78  4965.5 1762.33  4972.0 1759.73
  4977.5 1758.67  4982.0 1758.54  4982.5 1758.04  4991.7 1758.04  4992.2 1758.54
  5008.6 1759.87  5019.2 1760.28  5040.3 1762.42  5082.6 1762.42  5095.0 1763.14
  5146.0 1764.74  5240.9 1765.28  5251.7 1765.55  5315.1 1765.80  5336.1 1765.67
#Mann=3,-1,0
  4721.0   0.035       0  4982.0   0.035       0  4992.2   0.035       0
Bank Sta=4982,4992.2
Exp/Cntr=0.3,0.1

Type RM Length L Ch R = 1,1755,450,450,450
BEGIN DESCRIPTION:
Mapping XS 96e63542
END DESCRIPTION:
XS GIS Cut Line= 3
      1660370.70      6934719.71      1660518.19      6935075.63
      1660620.34      6935406.04
#Sta/Elev= 30
  4615.2 1767.65  4669.2 1767.15  4746.3 1765.26  4770.2 1764.52  4808.2 1762.19
  4840.7 1761.22  4871.2 1761.94  4876.6 1762.30  4884.0 1761.84  4929.7 1762.20
  4948.2 1761.18  4977.5 1760.80  4992.2 1760.21  5003.5 1760.12  5013.4 1760.96
  5023.9 1761.16  5040.0 1760.66  5045.2 1760.81  5072.6 1759.87  5092.0 1759.83
  5092.5 1759.33  5101.7 1759.33  5102.2 1759.83  5105.3 1759.95  5118.1 1761.89
  5128.5 1763.06  5137.9 1763.75  5254.2 1764.37  5264.6 1764.16  5346.3 1764.37
#Mann=3,-1,0
  4615.2   0.035       0  5092.0   0.035       0  5102.2   0.035       0
Bank Sta=5092,5102.2
Exp/Cntr=0.3,0.1

Type RM Length L Ch R = 1,1305,46,46,46
BEGIN DESCRIPTION:
Mapping XS e540ea53
END DESCRIPTION:
XS GIS Cut Line= 4
      1660045.47      6934857.11      1660176.69      6934965.42
      1660278.78      6935049.44      1660565.49      6935342.29
#Sta/Elev= 30
  4829.8 1764.25  4886.9 1764.26  4901.2 1768.26  4915.5 1766.97  4929.9 1764.45
  4936.4 1764.25  4944.2 1763.19  4971.8 1756.54  4979.4 1755.79  5008.1 1755.04
  5014.5 1755.58  5022.4 1755.17  5028.9 1756.16  5036.6 1755.16  5052.4 1754.92
  5052.9 1754.42  5062.2 1754.42  5062.7 1754.92  5064.0 1755.57  5086.3 1756.24
  5121.4 1761.01  5142.7 1761.74  5206.3 1762.55  5241.7 1762.27  5340.6 1763.04
  5347.7 1762.63  5383.0 1763.00  5404.3 1762.57  5411.3 1763.04  5542.0 1763.78
#Mann=3,-1,0
  4829.8   0.035       0  5052.4   0.035       0  5062.7   0.035       0
Bank Sta=5052.4,5062.7
Exp/Cntr=0.3,0.1

Type RM Length L Ch R = 1,1259,38,38,38
BEGIN DESCRIPTION:
Mapping XS 5f6be70e
END DESCRIPTION:
XS GIS Cut Line= 3
      1660039.17      6934918.87      1660144.75      6934998.75
      1660559.83      6935427.84
#Sta/Elev= 30
  4868.5 1763.96  4922.4 1763.92  4957.8 1768.58  4997.9 1770.18  5003.9 1770.18
  5007.6 1769.02  5014.6 1770.76  5021.8 1768.83  5028.7 1770.90  5035.9 1768.38
  5042.9 1770.81  5050.1 1768.04  5057.0 1770.69  5064.2 1767.63  5071.2 1770.25
  5078.4 1766.48  5085.3 1770.10  5092.5 1766.62  5099.5 1769.11  5106.7 1765.43
  5113.6 1768.14  5120.8 1765.02  5127.8 1766.66  5135.0 1764.63  5141.9 1765.02
  5149.1 1763.49  5186.4 1761.32  5186.9 1760.82  5196.7 1761.32  5597.9 1763.71
#Mann=3,-1,0
  4868.5   0.035       0  5186.4   0.035       0  5196.7   0.035       0
Bank Sta=5186.4,5196.7
Exp/Cntr=0.3,0.1

Type RM Length L Ch R = 1,1221,195,195,195
BEGIN DESCRIPTION:
Mapping XS 9a62c1bf
END DESCRIPTION:
XS GIS Cut Line= 4
      1660007.92      6934963.32      1660119.06      6935025.83
      1660195.44      6935100.83      1660480.68      6935548.53
#Sta/Elev= 30
  4873.8 1763.42  4977.3 1763.95  4985.2 1763.38  4993.2 1761.97  4998.4 1759.98
  5007.1 1759.53  5014.1 1756.80  5021.2 1757.97  5023.1 1756.32  5023.6 1755.82
  5032.9 1755.82  5033.4 1756.32  5035.4 1757.64  5042.4 1756.56  5049.5 1758.43
  5056.5 1758.64  5063.7 1759.70  5141.0 1761.42  5213.8 1760.96  5223.1 1760.51
  5344.1 1762.17  5395.7 1761.86  5425.1 1762.36  5432.1 1761.84  5453.3 1762.47
  5474.5 1761.60  5541.3 1762.93  5555.6 1762.53  5620.1 1762.96  5639.2 1763.54
#Mann=3,-1,0
  4873.8   0.035       0  5023.1   0.035       0  5033.4   0.035       0
Bank Sta=5023.1,5033.4
Exp/Cntr=0.3,0.1

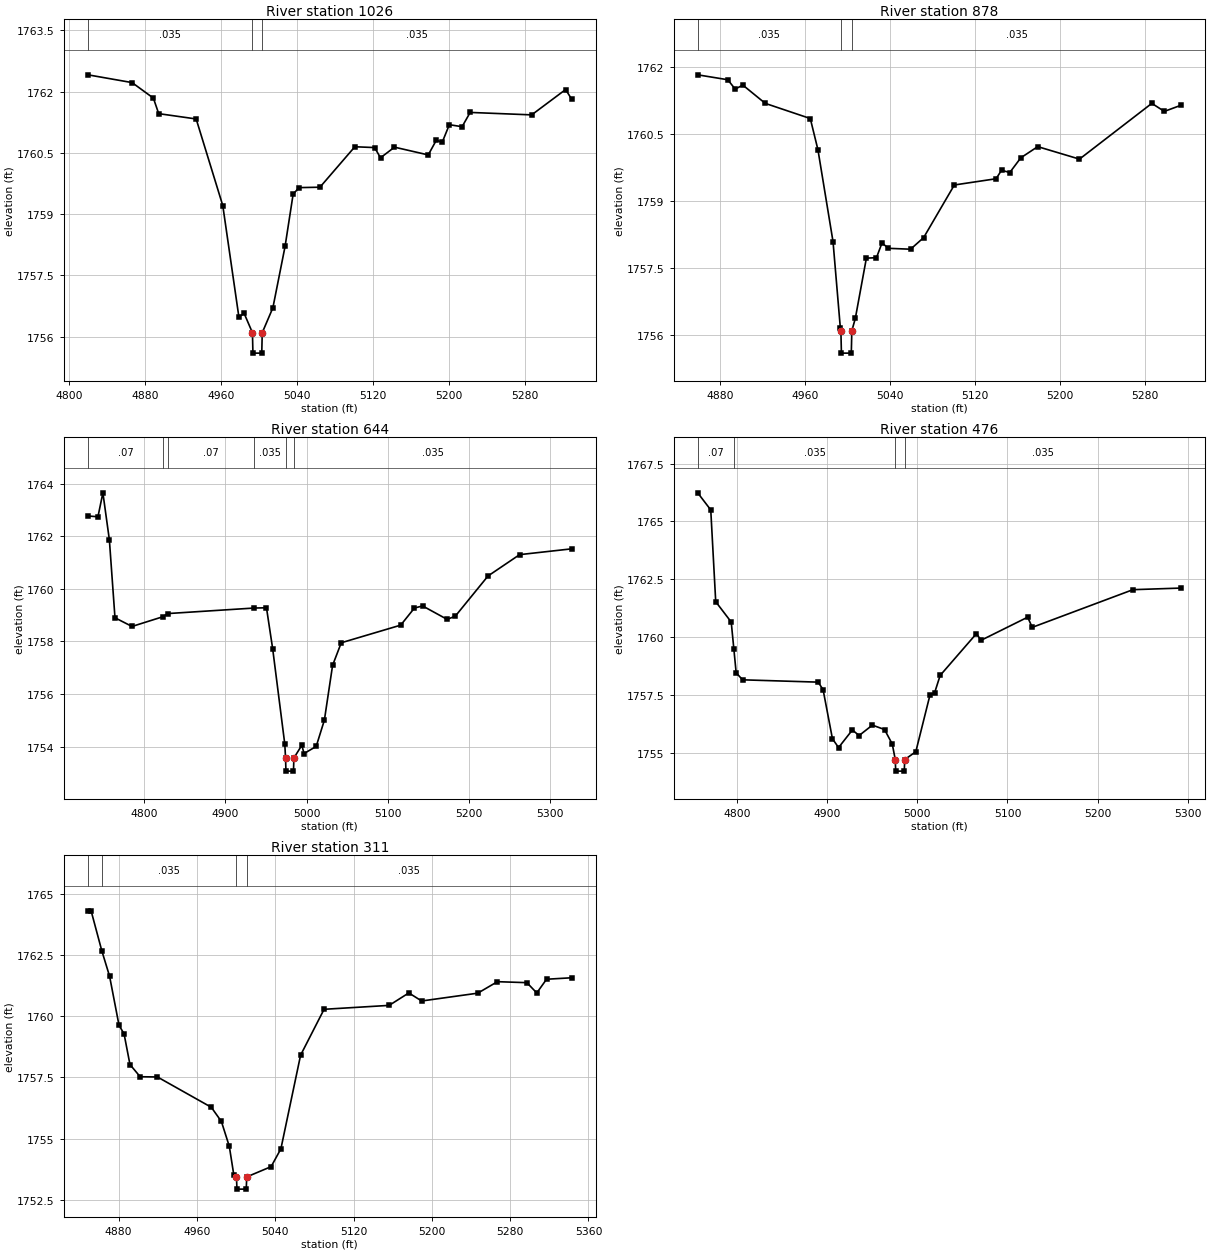
Type RM Length L Ch R = 1,1026,148,148,148
BEGIN DESCRIPTION:
Mapping XS 02274acb
END DESCRIPTION:
XS GIS Cut Line= 3
      1659921.75      6935130.88      1660083.20      6935210.30
      1660348.88      6935403.81
#Sta/Elev= 30
  4820.0 1762.41  4866.4 1762.22  4888.8 1761.84  4894.4 1761.46  4933.8 1761.33
  4961.8 1759.21  4978.7 1756.49  4984.3 1756.57  4993.0 1756.10  4993.5 1755.60
  5002.8 1755.60  5003.3 1756.10  5014.5 1756.71  5027.3 1758.21  5035.8 1759.49
  5042.0 1759.65  5064.0 1759.66  5100.7 1760.65  5121.5 1760.63  5127.7 1760.38
  5142.4 1760.64  5177.9 1760.45  5186.4 1760.81  5192.6 1760.76  5200.1 1761.19
  5213.5 1761.14  5222.0 1761.49  5286.7 1761.43  5322.4 1762.05  5328.6 1761.82
#Mann=3,-1,0
  4820.0   0.035       0  4993.0   0.035       0  5003.3   0.035       0
Bank Sta=4993,5003.3
Exp/Cntr=0.3,0.1

Type RM Length L Ch R = 1,878,234,234,234
BEGIN DESCRIPTION:
Mapping XS 7f71a855
END DESCRIPTION:
XS GIS Cut Line= 3
      1659879.98      6935212.98      1659977.86      6935314.47
      1660280.35      6935399.46
#Sta/Elev= 30
  4859.0 1761.83  4887.3 1761.72  4894.3 1761.51  4901.5 1761.60  4922.6 1761.19
  4965.0 1760.85  4972.2 1760.15  4986.4 1758.09  4993.3 1756.15  4993.8 1756.09
  4994.3 1755.59  5003.6 1755.59  5004.1 1756.09  5007.4 1756.37  5017.8 1757.72
  5027.3 1757.73  5032.5 1758.06  5038.6 1757.94  5059.4 1757.92  5071.7 1758.18
  5100.6 1759.36  5139.9 1759.50  5145.0 1759.69  5152.8 1759.64  5163.2 1759.97
  5179.1 1760.22  5218.4 1759.94  5286.5 1761.19  5298.3 1761.01  5314.2 1761.15
#Mann=3,-1,0
  4859.0   0.035       0  4993.8   0.035       0  5004.1   0.035       0
Bank Sta=4993.8,5004.1
Exp/Cntr=0.3,0.1

Type RM Length L Ch R = 1,644,168,168,168
BEGIN DESCRIPTION:
Mapping XS 5184c36b
END DESCRIPTION:
XS GIS Cut Line= 3
      1659840.74      6935749.78      1659991.90      6935528.22
      1660317.03      6935485.04
#Sta/Elev= 30
  4730.5 1762.77  4742.8 1762.74  4748.9 1763.65  4756.9 1761.86  4763.8 1758.90
  4784.8 1758.57  4822.9 1758.94  4828.9 1759.06  4935.3 1759.27  4950.6 1759.28
  4958.2 1757.73  4973.2 1754.09  4974.1 1753.57  4974.6 1753.07  4983.9 1753.07
  4984.4 1753.57  4994.1 1754.05  4997.0 1753.74  5011.9 1754.01  5022.0 1755.01
  5032.1 1757.09  5042.8 1757.95  5116.1 1758.62  5133.0 1759.27  5143.1 1759.35
  5173.3 1758.84  5183.4 1758.96  5223.8 1760.49  5262.7 1761.30  5326.7 1761.52
#Mann=6,-1,0
  4730.5    0.07       0  4822.9   0.035       0  4828.9    0.07       0
  4935.3   0.035       0  4974.1   0.035       0  4984.4   0.035       0
Bank Sta=4974.1,4984.4
Exp/Cntr=0.3,0.1

Type RM Length L Ch R = 1,476,165,165,165
BEGIN DESCRIPTION:
Mapping XS 8c2555a1
END DESCRIPTION:
XS GIS Cut Line= 3
      1659879.97      6935740.65      1660098.58      6935636.77
      1660387.61      6935580.48
#Sta/Elev= 30
  4756.3 1766.24  4770.8 1765.50  4776.3 1761.53  4793.5 1760.65  4796.4 1759.49
  4799.0 1758.45  4806.2 1758.15  4889.9 1758.05  4895.4 1757.73  4905.8 1755.60
  4912.6 1755.22  4927.9 1755.98  4935.4 1755.74  4950.1 1756.19  4963.6 1756.00
  4972.2 1755.37  4975.5 1754.70  4976.0 1754.20  4985.5 1754.20  4986.0 1754.70
  4998.3 1755.04  5014.0 1757.49  5019.1 1757.58  5025.3 1758.34  5065.6 1760.15
  5070.7 1759.86  5122.4 1760.86  5127.5 1760.42  5239.2 1762.05  5292.8 1762.12
#Mann=4,-1,0
  4756.3    0.07       0  4796.4   0.035       0  4975.5   0.035       0
  4986.0   0.035       0
Bank Sta=4975.5,4986
Exp/Cntr=0.3,0.1

Type RM Length L Ch R = 1,311,137,137,137
BEGIN DESCRIPTION:
Mapping XS 52fd3c67
END DESCRIPTION:
XS GIS Cut Line= 3
      1659913.72      6935743.25      1660059.00      6935783.99
      1660400.36      6935818.66
#Sta/Elev= 30
  4848.7 1764.32  4851.9 1764.32  4862.8 1762.69  4870.8 1761.64  4880.4 1759.64
  4885.6 1759.28  4891.6 1758.03  4902.0 1757.53  4919.7 1757.52  4974.7 1756.28
  4985.0 1755.70  4993.1 1754.68  4997.7 1753.51  5000.4 1753.43  5000.9 1752.93
  5010.4 1752.93  5010.9 1753.43  5035.8 1753.85  5045.8 1754.58  5065.9 1758.41
  5089.9 1760.29  5156.4 1760.45  5176.5 1760.96  5189.6 1760.63  5246.9 1760.95
  5267.0 1761.42  5297.1 1761.38  5307.2 1760.96  5317.2 1761.52  5342.7 1761.58
#Mann=4,-1,0
  4848.7    0.07       0  4862.8   0.035       0  5000.4   0.035       0
  5010.9   0.035       0
Bank Sta=5000.4,5010.9
Exp/Cntr=0.3,0.1