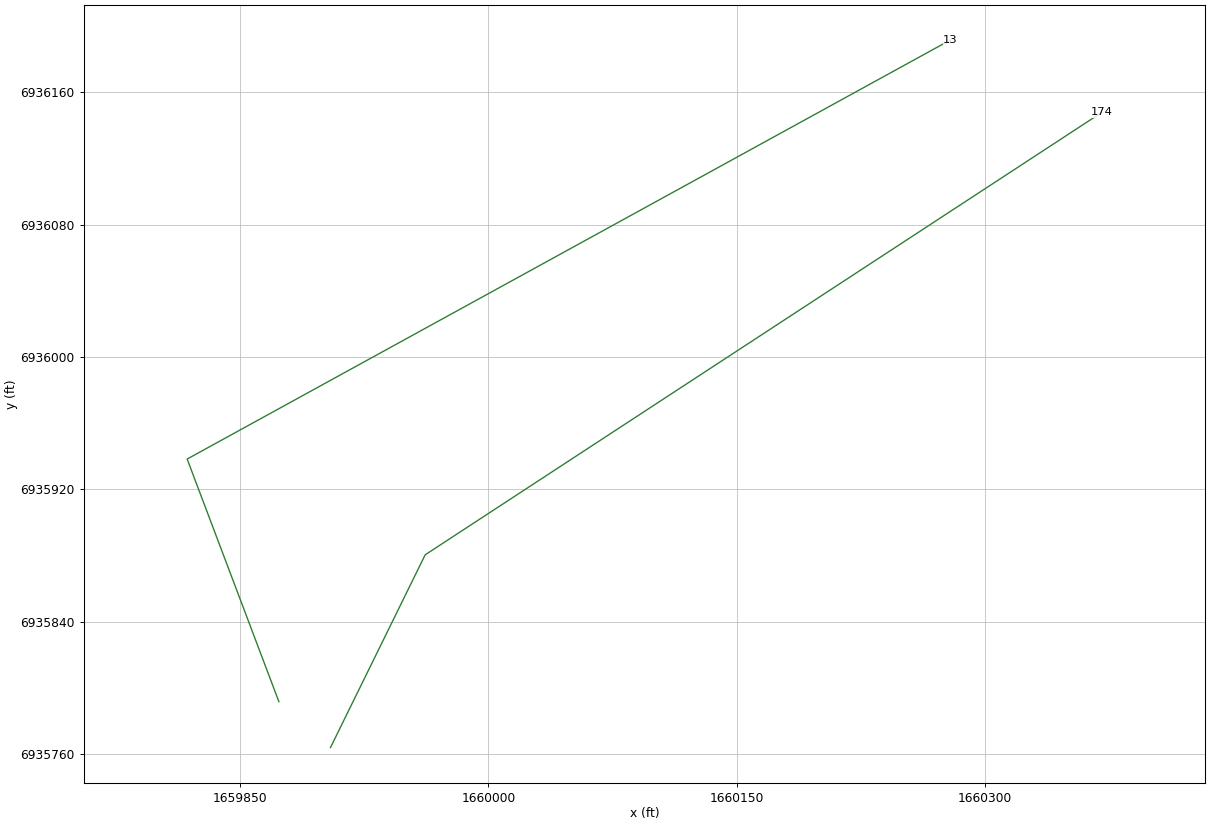
HEC-RAS study Chimney Creek 1099.prj: Chimney Creek 1099 Base Level Engineering

--- Chimney Creek 1099.g01 (geometry) --- (continued)

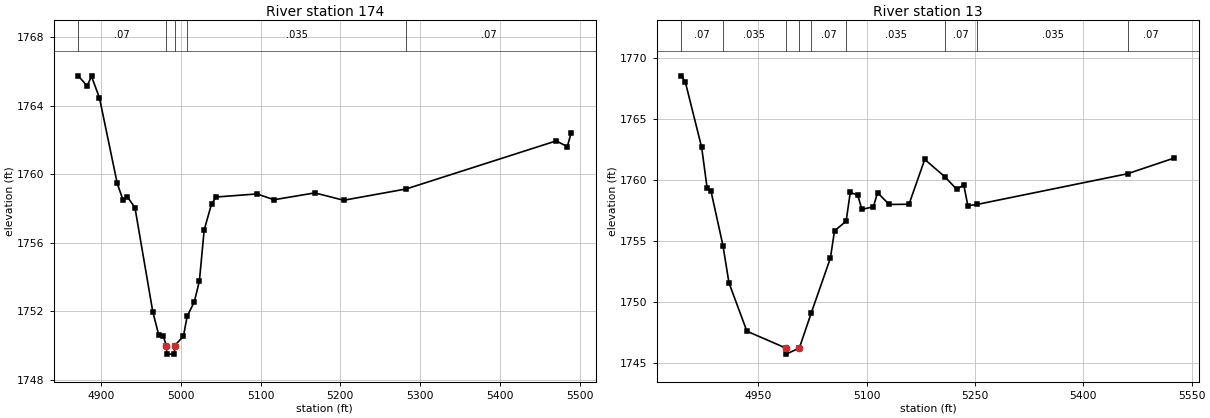
Type RM Length L Ch R = 1,174,161,161,161
BEGIN DESCRIPTION:
Mapping XS 7a955471
END DESCRIPTION:
XS GIS Cut Line= 3
      1659904.55      6935764.06      1659961.77      6935880.52
      1660370.58      6936147.83
#Sta/Elev= 30
  4871.2 1765.76  4882.4 1765.17  4887.9 1765.73  4897.9 1764.47  4920.2 1759.47
  4927.3 1758.52  4932.9 1758.69  4942.4 1758.06  4964.7 1751.99  4972.3 1750.60
  4977.8 1750.56  4981.8 1750.00  4982.3 1749.50  4991.8 1749.50  4992.3 1750.00
  5003.2 1750.55  5007.9 1751.72  5016.8 1752.55  5023.2 1753.77  5029.2 1756.75
  5038.4 1758.27  5044.3 1758.68  5095.6 1758.86  5116.7 1758.52  5168.0 1758.92
  5204.2 1758.49  5282.5 1759.15  5470.8 1761.96  5484.6 1761.62  5489.4 1762.42
#Mann=5,-1,0
  4871.2    0.07       0  4981.8    0.07       0  4992.3    0.07       0
  5007.9   0.035       0  5282.5    0.07       0
Bank Sta=4981.8,4992.3
Exp/Cntr=0.3,0.1

Type RM Length L Ch R = 1,13,0,0,0
BEGIN DESCRIPTION:
Chimney Creek 1099 1.0
END DESCRIPTION:
XS GIS Cut Line= 3
      1659873.38      6935791.81      1659817.96      6935938.38
      1660279.12      6936191.59
#Sta/Elev= 30
  4843.3 1768.54  4848.7 1768.02  4871.3 1762.67  4878.9 1759.31  4884.2 1759.09
  4900.8 1754.63  4909.1 1751.58  4933.9 1747.62  4987.7 1746.24  4988.2 1745.74
  5006.6 1746.24  5023.0 1749.10  5049.6 1753.61  5055.3 1755.84  5071.4 1756.63
  5077.1 1758.99  5087.4 1758.77  5093.2 1757.60  5109.2 1757.81  5114.9 1758.97
  5131.0 1758.00  5158.5 1758.02  5180.3 1761.69  5208.1 1760.27  5224.8 1759.23
  5234.3 1759.62  5240.0 1757.90  5253.3 1758.01  5461.3 1760.52  5526.1 1761.81
#Mann=9,-1,0
  4843.3    0.07       0  4900.8   0.035       0  4987.7   0.035       0
  5006.6   0.035       0  5023.0    0.07       0  5071.4   0.035       0
  5208.1    0.07       0  5253.3   0.035       0  5461.3    0.07       0
Bank Sta=4987.7,5006.6
Exp/Cntr=0.3,0.1

Chan Stop Cuts=-1