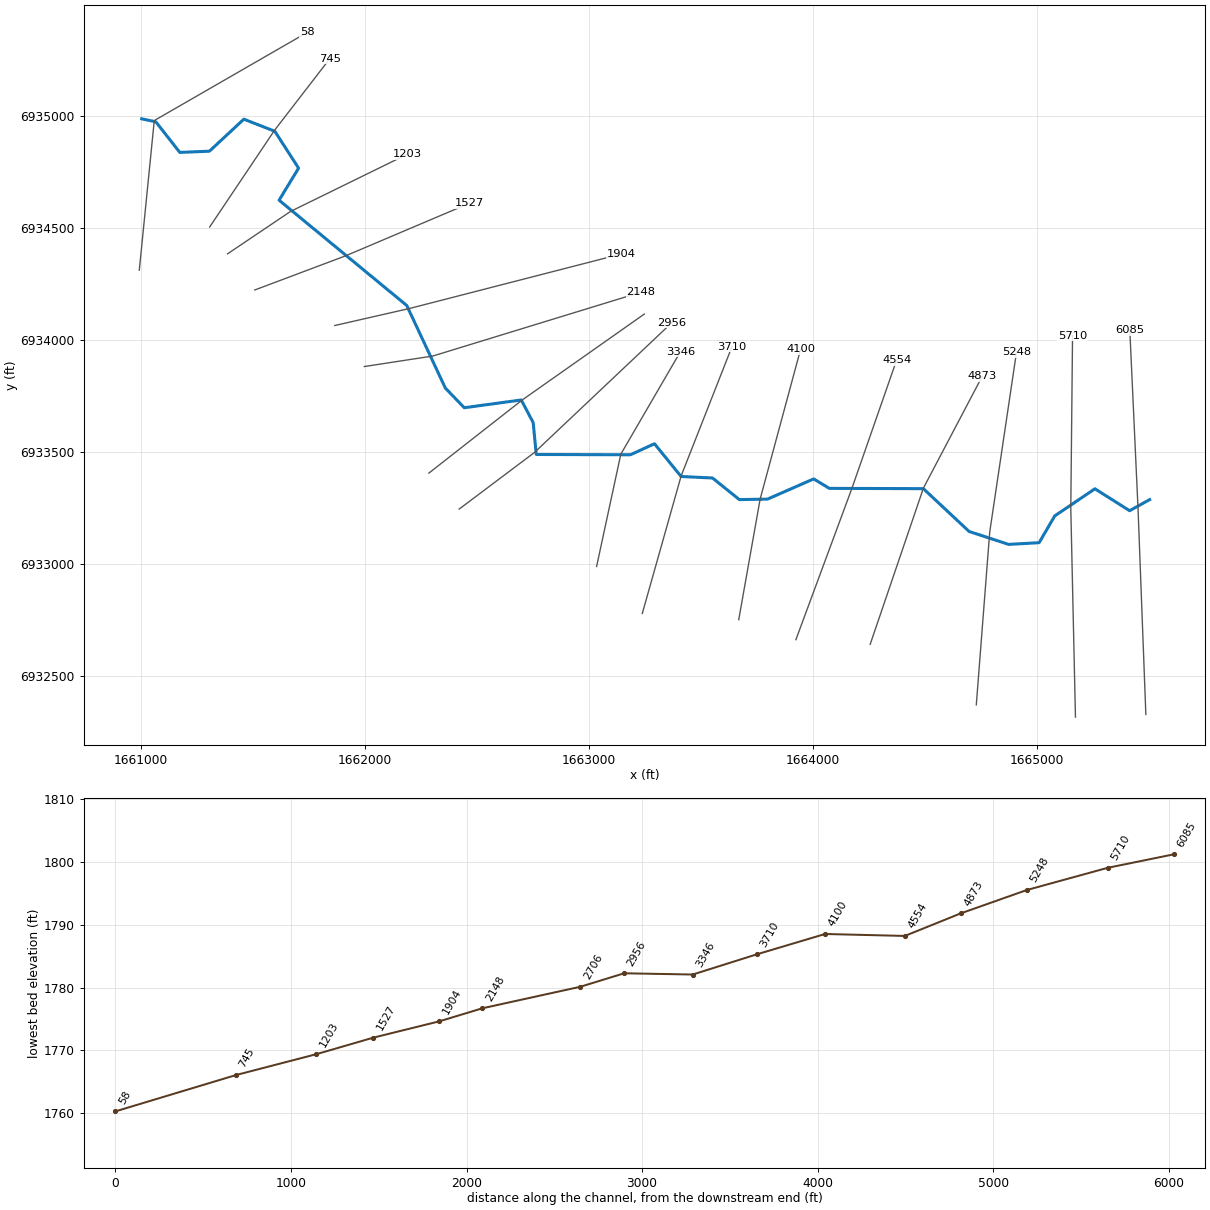
--- Chimney Creek 1100.prj (project) ---

Proj Title=Chimney Creek 1100 Base Level Engineering
Current Plan=p01
Default Exp/Contr=0.3,0.1
English Units
Geom File=g01
Flow File=f01
Plan File=p01
BEGIN DESCRIPTION:
Chimney Creek 1100
END DESCRIPTION:

--- Chimney Creek 1100.p01 (plan) ---

Plan Title=Multiple Run
Short Identifier=Multiple
Geom File=g01
Flow File=f01
Subcritical Flow
K Sum by GR= 0
Std Step Tol= 0.01
Critical Tol= 0.01
Num of Std Step Trials= 20
Max Error Tol= 0.3
Flow Tol Ratio= 0.001
Split Flow NTrial= 30
Split Flow Tol= 0.02
Split Flow Ratio= 0.02
Log Output Level= 0
Friction Slope Method= 1
Unsteady Friction Slope Method= 2
Unsteady Bridges Friction Slope Method= 1
Parabolic Critical Depth
Global Vel Dist=  1 , 1 , 1
Global Log Level= 0
CheckData=True
Encroach Param= -1, 0, 0, 0
BEGIN DESCRIPTION:
Multiple Run
END DESCRIPTION:

--- Chimney Creek 1100.f01 (steady flow) ---

Flow Title=Multiple
Number of Profiles=7
Profile Names=10-year,25-year,50-year,1pct_min,100-year,1pct_plu,500-year
River Rch & RM= Chimney Creek 11,Reach-1,6085
     245     338     416     254     508    1013     767
River Rch & RM= Chimney Creek 11,Reach-1,4554
     282     393     484     297     593    1184     902
Boundary for River Rch & Prof#=Chimney Creek 11,Reach-1,1
Up Type=0
Dn Type=3
Dn Slope=0.005
Boundary for River Rch & Prof#=Chimney Creek 11,Reach-1,2
Up Type=0
Dn Type=3
Dn Slope=0.005
Boundary for River Rch & Prof#=Chimney Creek 11,Reach-1,3
Up Type=0
Dn Type=3
Dn Slope=0.005
Boundary for River Rch & Prof#=Chimney Creek 11,Reach-1,4
Up Type=0
Dn Type=3
Dn Slope=0.005
Boundary for River Rch & Prof#=Chimney Creek 11,Reach-1,5
Up Type=0
Dn Type=3
Dn Slope=0.005
Boundary for River Rch & Prof#=Chimney Creek 11,Reach-1,6
Up Type=0
Dn Type=3
Dn Slope=0.005
Boundary for River Rch & Prof#=Chimney Creek 11,Reach-1,7
Up Type=0
Dn Type=3
Dn Slope=0.005

--- Chimney Creek 1100.g01 (geometry) ---

Geom Title=Existing Conditions

River Reach=Chimney Creek 11,Reach-1
Reach XY= 30
      1665505.00      6933288.00      1665415.55      6933238.50
      1665260.64      6933336.30      1665081.17      6933215.13
      1665011.47      6933095.69      1664875.04      6933088.05
      1664698.83      6933145.86      1664494.57      6933336.95
      1664074.98      6933338.18      1664005.00      6933380.44
      1663799.06      6933290.25      1663673.23      6933288.07
      1663553.52      6933384.44      1663413.01      6933391.24
      1663294.39      6933537.41      1663186.74      6933488.23
      1662766.49      6933489.48      1662752.76      6933632.08
      1662699.59      6933732.84      1662445.29      6933698.18
      1662360.83      6933785.69      1662188.36      6934154.68
      1661618.41      6934624.66      1661705.47      6934767.84
      1661599.39      6934932.41      1661461.04      6934986.39
      1661307.44      6934843.45      1661175.20      6934838.02
      1661068.31      6934974.54      1661005.00      6934988.00

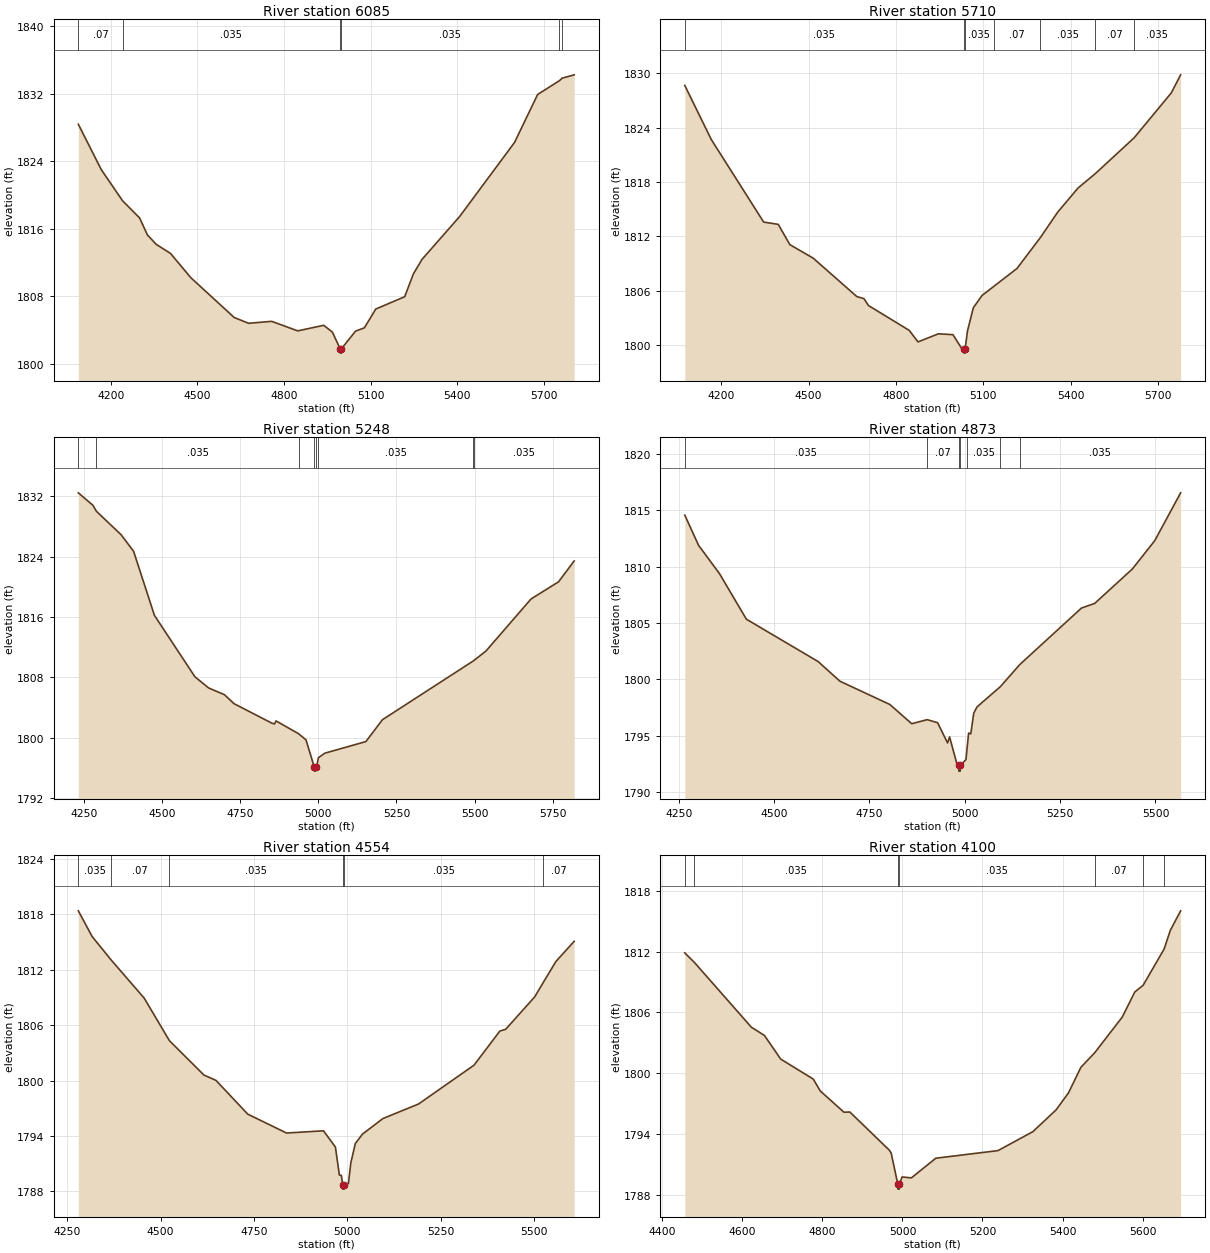
Type RM Length L Ch R = 1,6085,375,375,375
BEGIN DESCRIPTION:
Chimney Creek 1100 12.0
END DESCRIPTION:
XS GIS Cut Line= 3
      1665487.97      6932328.82      1665453.38      6933240.67
      1665416.41      6934044.22
#Sta/Elev= 30
  4087.5 1828.40  4166.7 1823.03  4240.5 1819.33  4299.8 1817.28  4326.8 1815.27
  4356.9 1814.16  4406.9 1813.07  4477.0 1810.20  4627.1 1805.48  4677.1 1804.79
  4757.2 1805.02  4847.2 1803.89  4937.3 1804.55  4967.3 1803.74  4994.2 1801.75
  4994.4 1801.25  4997.9 1801.25  4998.2 1801.75  5047.4 1803.86  5078.0 1804.25
  5117.5 1806.48  5217.6 1807.94  5247.6 1810.64  5277.6 1812.37  5407.8 1817.45
  5598.0 1826.24  5678.0 1831.93  5753.6 1833.57  5762.6 1833.86  5804.4 1834.26
#Mann=6,-1,0
  4087.5    0.07       0  4240.5   0.035       0  4994.2   0.035       0
  4998.2   0.035       0  5753.6    0.07       0  5762.6   0.035       0
Bank Sta=4994.2,4998.2
Exp/Cntr=0.3,0.1

Type RM Length L Ch R = 1,5710,462,462,462
BEGIN DESCRIPTION:
Mapping XS 73b46bb0
END DESCRIPTION:
XS GIS Cut Line= 3
      1665173.74      6932317.05      1665152.90      6933249.35
      1665160.72      6934020.18
#Sta/Elev= 30
  4074.9 1828.65  4165.9 1822.68  4345.9 1813.57  4395.9 1813.32  4435.9 1811.08
  4516.0 1809.59  4666.0 1805.35  4690.4 1805.12  4706.0 1804.36  4846.0 1801.62
  4876.1 1800.35  4946.1 1801.24  4996.1 1801.15  5026.1 1799.63  5034.1 1799.61
  5034.3 1799.11  5037.8 1799.11  5038.1 1799.61  5046.1 1801.56  5066.1 1804.11
  5096.1 1805.47  5135.8 1806.46  5216.1 1808.45  5296.4 1811.86  5356.1 1814.67
  5426.1 1817.34  5484.6 1818.90  5618.3 1822.86  5746.1 1827.82  5778.3 1829.82
#Mann=7,-1,0
  4074.9   0.035       0  5034.1   0.035       0  5038.1   0.035       0
  5135.8    0.07       0  5296.4   0.035       0  5484.6    0.07       0
  5618.3   0.035       0
Bank Sta=5034.1,5038.1
Exp/Cntr=0.3,0.1

Type RM Length L Ch R = 1,5248,375,375,375
BEGIN DESCRIPTION:
Mapping XS e8515b09
END DESCRIPTION:
XS GIS Cut Line= 3
      1664731.03      6932371.73      1664790.92      6933142.58
      1664910.71      6933947.24
#Sta/Elev= 30
  4232.2 1832.48  4278.6 1830.84  4290.1 1830.03  4368.9 1826.93  4409.0 1824.73
  4475.7 1816.23  4605.4 1808.07  4649.7 1806.58  4699.9 1805.70  4730.0 1804.52
  4850.3 1801.95  4859.9 1801.81  4864.9 1802.22  4936.8 1800.53  4960.7 1799.71
  4987.6 1796.06  4987.8 1795.56  4991.3 1795.56  4991.6 1796.06  4994.6 1796.11
  5000.5 1797.34  5021.0 1797.94  5152.4 1799.48  5205.4 1802.38  5495.1 1810.15
  5496.9 1810.20  5536.6 1811.49  5680.7 1818.39  5769.1 1820.68  5818.9 1823.44
#Mann=8,-1,0
  4232.2    0.07       0  4290.1   0.035       0  4936.8    0.07       0
  4987.6    0.07       0  4991.6    0.07       0  5000.5   0.035       0
  5495.1    0.07       0  5496.9   0.035       0
Bank Sta=4987.6,4991.6
Exp/Cntr=0.3,0.1

Type RM Length L Ch R = 1,4873,319,319,319
BEGIN DESCRIPTION:
Mapping XS 8f075f2d
END DESCRIPTION:
XS GIS Cut Line= 3
      1664257.30      6932641.96      1664495.13      6933339.84
      1664757.28      6933838.09
#Sta/Elev= 30
  4265.7 1814.58  4301.8 1811.90  4356.6 1809.39  4427.2 1805.34  4615.3 1801.58
  4672.7 1799.83  4803.3 1797.77  4860.8 1796.06  4901.3 1796.42  4928.7 1796.15
  4954.8 1794.35  4960.1 1794.89  4979.9 1792.42  4984.1 1792.35  4984.4 1791.85
  4987.9 1791.85  4988.1 1792.35  5003.0 1792.87  5006.2 1793.95  5010.0 1795.23
  5015.7 1795.16  5023.5 1797.00  5032.0 1797.55  5093.3 1799.35  5143.8 1801.30
  5306.0 1806.33  5340.6 1806.74  5439.5 1809.80  5498.1 1812.31  5566.0 1816.56
#Mann=7,-1,0
  4265.7   0.035       0  4901.3    0.07       0  4984.1    0.07       0
  4988.1    0.07       0  5006.2   0.035       0  5093.3    0.07       0
  5143.8   0.035       0
Bank Sta=4984.1,4988.1
Exp/Cntr=0.3,0.1

Type RM Length L Ch R = 1,4554,454,454,454
BEGIN DESCRIPTION:
Mapping XS 946d6ce3
END DESCRIPTION:
XS GIS Cut Line= 3
      1663925.68      6932662.74      1664175.69      6933338.11
      1664375.35      6933911.06
#Sta/Elev= 30
  4280.0 1818.36  4316.8 1815.59  4367.5 1813.06  4456.2 1808.92  4523.8 1804.31
  4616.2 1800.59  4648.2 1800.02  4733.5 1796.36  4837.2 1794.32  4936.1 1794.56
  4968.0 1792.80  4978.6 1789.78  4983.9 1789.73  4987.3 1788.75  4987.6 1788.25
  4991.1 1788.25  4991.4 1788.75  5002.7 1788.85  5009.3 1791.10  5021.2 1793.18
  5040.4 1794.20  5095.3 1795.89  5190.5 1797.46  5338.9 1801.66  5408.0 1805.35
  5423.6 1805.54  5501.3 1809.05  5523.2 1810.54  5558.1 1812.88  5606.9 1815.06
#Mann=6,-1,0
  4280.0   0.035       0  4367.5    0.07       0  4523.8   0.035       0
  4987.3   0.035       0  4991.4   0.035       0  5523.2    0.07       0
Bank Sta=4987.3,4991.4
Exp/Cntr=0.3,0.1

Type RM Length L Ch R = 1,4100,390,390,390
BEGIN DESCRIPTION:
Mapping XS ea219b54
END DESCRIPTION:
XS GIS Cut Line= 3
      1663670.48      6932751.96      1663765.97      6933290.19
      1663946.52      6933958.60
#Sta/Elev= 30
  4456.1 1811.87  4480.3 1810.92  4622.4 1804.54  4655.2 1803.72  4695.8 1801.39
  4777.1 1799.42  4794.6 1798.25  4853.7 1796.15  4868.5 1796.17  4966.8 1792.42
  4971.8 1792.13  4988.3 1789.06  4988.6 1788.56  4992.2 1788.56  4992.4 1789.06
  4999.1 1789.76  5022.3 1789.67  5083.3 1791.61  5238.7 1792.36  5325.9 1794.23
  5383.7 1796.37  5414.8 1798.05  5445.9 1800.58  5480.7 1802.03  5549.5 1805.55
  5580.5 1808.01  5601.3 1808.67  5653.9 1812.25  5669.3 1814.09  5695.1 1816.02
#Mann=7,-1,0
  4456.1    0.07       0  4480.3   0.035       0  4988.3   0.035       0
  4992.4   0.035       0  5480.7    0.07       0  5601.3   0.035       0
  5653.9    0.07       0
Bank Sta=4988.3,4992.4
Exp/Cntr=0.3,0.1

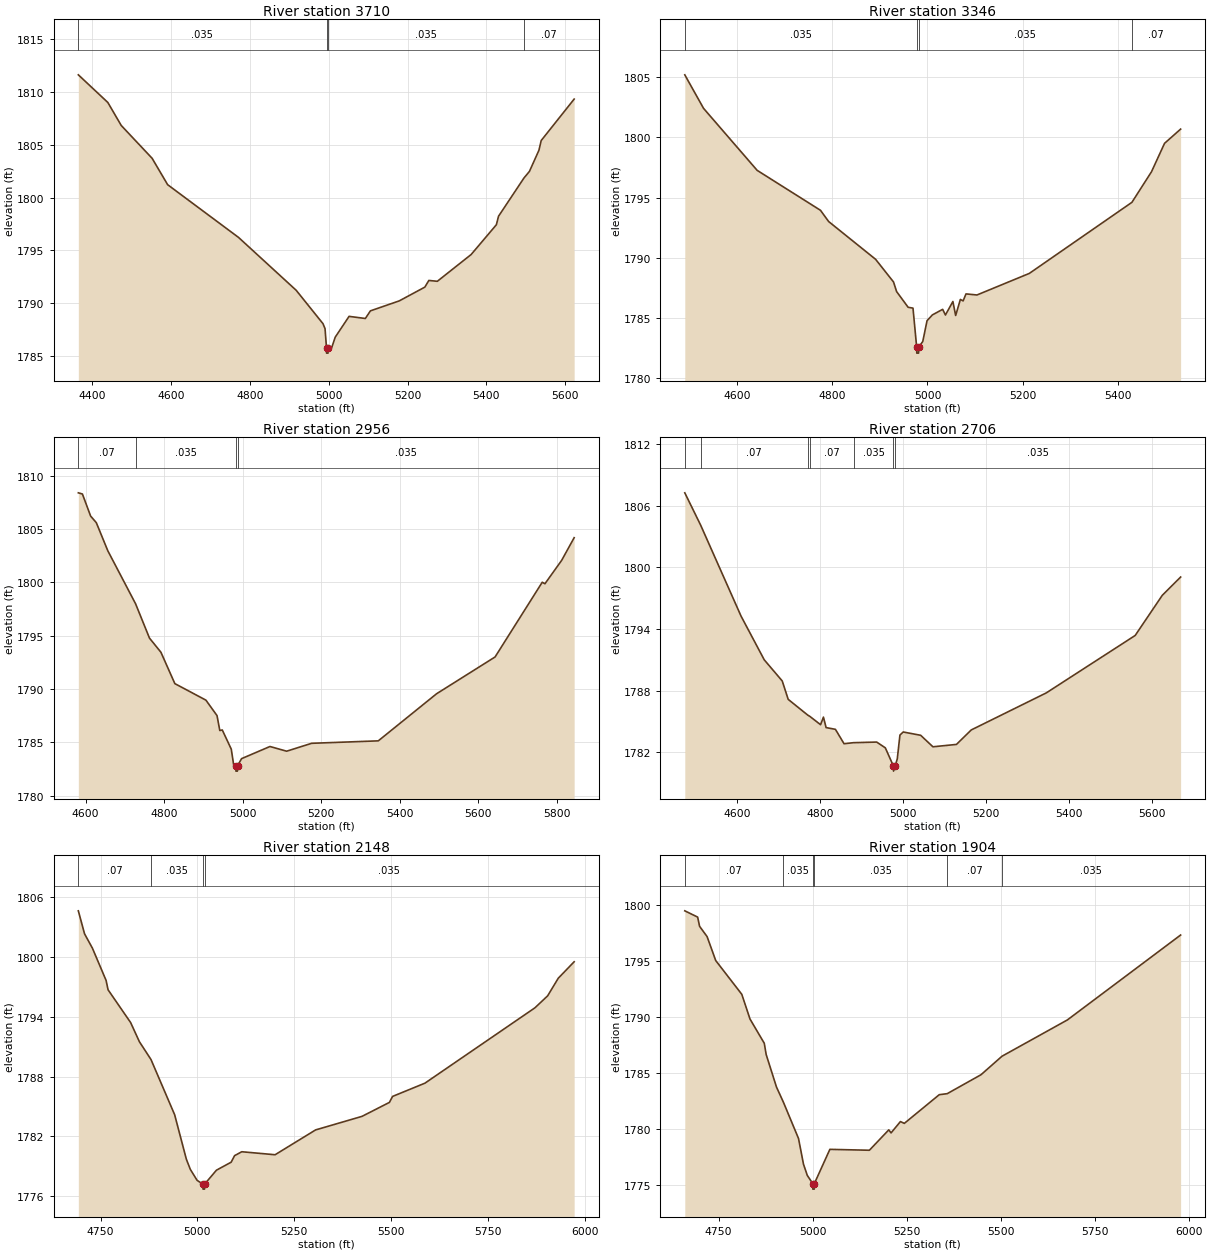
Type RM Length L Ch R = 1,3710,364,364,364
BEGIN DESCRIPTION:
Mapping XS d1c95197
END DESCRIPTION:
XS GIS Cut Line= 3
      1663239.93      6932779.80      1663413.54      6933394.36
      1663640.47      6933971.22
#Sta/Elev= 30
  4364.4 1811.58  4439.3 1808.97  4473.3 1806.80  4551.7 1803.70  4591.1 1801.21
  4771.1 1796.23  4917.4 1791.24  4985.4 1788.09  4990.6 1787.62  4994.3 1785.81
  4994.5 1785.31  4998.2 1785.31  4998.5 1785.81  5007.6 1785.84  5016.5 1786.82
  5051.6 1788.78  5092.9 1788.58  5105.8 1789.30  5178.9 1790.24  5243.9 1791.54
  5254.1 1792.17  5275.6 1792.09  5361.5 1794.62  5425.5 1797.43  5430.9 1798.23
  5495.7 1801.85  5509.5 1802.47  5533.5 1804.46  5539.3 1805.38  5622.9 1809.29
#Mann=4,-1,0
  4364.4   0.035       0  4994.3   0.035       0  4998.5   0.035       0
  5495.7    0.07       0
Bank Sta=4994.3,4998.5
Exp/Cntr=0.3,0.1

Type RM Length L Ch R = 1,3346,390,390,390
BEGIN DESCRIPTION:
Mapping XS a05449b3
END DESCRIPTION:
XS GIS Cut Line= 3
      1663035.94      6932989.45      1663144.01      6933490.71
      1663409.63      6933947.75
#Sta/Elev= 30
  4490.3 1805.17  4529.7 1802.39  4642.3 1797.25  4775.3 1793.94  4792.4 1793.01
  4891.0 1789.88  4928.7 1788.00  4935.2 1787.20  4959.4 1785.90  4969.6 1785.83
  4977.3 1782.60  4977.6 1782.10  4981.3 1782.10  4981.5 1782.60  4990.1 1783.06
  4999.1 1784.79  5010.4 1785.27  5031.9 1785.73  5037.7 1785.26  5053.4 1786.38
  5059.2 1785.22  5069.1 1786.55  5074.9 1786.43  5080.9 1787.01  5104.0 1786.92
  5214.0 1788.71  5429.4 1794.60  5470.6 1797.14  5497.9 1799.49  5531.7 1800.67
#Mann=4,-1,0
  4490.3   0.035       0  4977.3   0.035       0  4981.5   0.035       0
  5429.4    0.07       0
Bank Sta=4977.3,4981.5
Exp/Cntr=0.3,0.1

Type RM Length L Ch R = 1,2956,250,250,250
BEGIN DESCRIPTION:
Mapping XS 39ddff7f
END DESCRIPTION:
XS GIS Cut Line= 3
      1662422.69      6933245.95      1662758.59      6933498.52
      1663370.94      6934077.08
#Sta/Elev= 30
  4581.4 1808.41  4591.8 1808.30  4612.7 1806.23  4627.2 1805.61  4656.4 1802.98
  4727.2 1798.00  4762.6 1794.78  4791.8 1793.45  4827.2 1790.51  4906.3 1788.96
  4934.6 1787.51  4941.7 1786.11  4948.0 1786.16  4970.9 1784.36  4977.1 1782.86
  4982.5 1782.80  4982.8 1782.30  4986.5 1782.30  4986.8 1782.80  4997.1 1783.47
  5069.4 1784.61  5111.9 1784.17  5175.6 1784.91  5345.3 1785.14  5493.8 1789.56
  5642.7 1793.01  5762.8 1800.02  5769.7 1799.88  5812.2 1802.07  5844.1 1804.20
#Mann=4,-1,0
  4581.4    0.07       0  4727.2   0.035       0  4982.5   0.035       0
  4986.8   0.035       0
Bank Sta=4982.5,4986.8
Exp/Cntr=0.3,0.1

Type RM Length L Ch R = 1,2706,558,558,558
BEGIN DESCRIPTION:
Mapping XS d8cd6901
END DESCRIPTION:
XS GIS Cut Line= 3
      1662287.21      6933406.41      1662703.90      6933732.81
      1663249.01      6934116.47
#Sta/Elev= 30
  4474.2 1807.25  4512.6 1804.09  4609.7 1795.26  4665.8 1790.99  4709.2 1788.93
  4723.6 1787.14  4770.6 1785.61  4776.2 1785.47  4801.7 1784.67  4808.6 1785.41
  4815.0 1784.39  4837.5 1784.22  4858.3 1782.82  4881.2 1782.92  4937.0 1782.98
  4957.8 1782.42  4977.4 1780.65  4977.7 1780.15  4981.7 1780.65  4986.7 1781.35
  4993.1 1783.66  5001.0 1783.96  5043.1 1783.64  5072.7 1782.52  5129.4 1782.75
  5165.1 1784.16  5346.2 1787.77  5560.5 1793.36  5625.9 1797.27  5670.1 1799.05
#Mann=7,-1,0
  4474.2   0.035       0  4512.6    0.07       0  4770.6   0.035       0
  4776.2    0.07       0  4881.2   0.035       0  4977.4   0.035       0
  4981.7   0.035       0
Bank Sta=4977.4,4981.7
Exp/Cntr=0.3,0.1

Type RM Length L Ch R = 1,2148,244,244,244
BEGIN DESCRIPTION:
Mapping XS 2cc18e0e
END DESCRIPTION:
XS GIS Cut Line= 3
      1661999.08      6933882.12      1662304.60      6933928.99
      1663233.44      6934213.72
#Sta/Elev= 30
  4692.5 1804.64  4708.6 1802.33  4728.8 1800.90  4764.2 1797.66  4769.3 1796.72
  4827.6 1793.43  4850.2 1791.51  4880.2 1789.72  4941.3 1784.18  4971.6 1779.71
  4981.8 1778.70  4999.3 1777.60  5014.3 1777.22  5014.6 1776.72  5018.4 1776.72
  5018.7 1777.22  5049.2 1778.62  5087.2 1779.42  5096.1 1780.08  5114.7 1780.47
  5200.7 1780.17  5305.3 1782.66  5425.2 1784.02  5495.9 1785.42  5504.1 1786.02
  5587.7 1787.35  5871.8 1794.91  5904.6 1796.11  5932.1 1797.88  5973.1 1799.53
#Mann=4,-1,0
  4692.5    0.07       0  4880.2   0.035       0  5014.3   0.035       0
  5018.7   0.035       0
Bank Sta=5014.3,5018.7
Exp/Cntr=0.3,0.1

Type RM Length L Ch R = 1,1904,377,377,377
BEGIN DESCRIPTION:
Mapping XS 802c63b7
END DESCRIPTION:
XS GIS Cut Line= 3
      1661867.23      6934065.27      1662202.34      6934141.67
      1663146.76      6934384.72
#Sta/Elev= 30
  4659.9 1799.49  4694.1 1798.93  4699.2 1798.11  4719.2 1797.19  4742.2 1795.05
  4811.5 1792.04  4833.4 1789.83  4871.3 1787.67  4876.4 1786.66  4903.8 1783.76
  4922.2 1782.41  4962.4 1779.17  4975.6 1776.88  4985.8 1775.87  5000.2 1775.15
  5000.5 1774.65  5004.3 1774.65  5004.6 1775.15  5045.8 1778.20  5150.9 1778.12
  5202.5 1779.94  5208.6 1779.67  5233.5 1780.68  5243.9 1780.52  5336.8 1783.08
  5357.9 1783.17  5447.8 1784.86  5503.6 1786.51  5677.5 1789.75  5978.8 1797.33
#Mann=6,-1,0
  4659.9    0.07       0  4922.2   0.035       0  5000.2   0.035       0
  5004.6   0.035       0  5357.9    0.07       0  5503.6   0.035       0
Bank Sta=5000.2,5004.6
Exp/Cntr=0.3,0.1

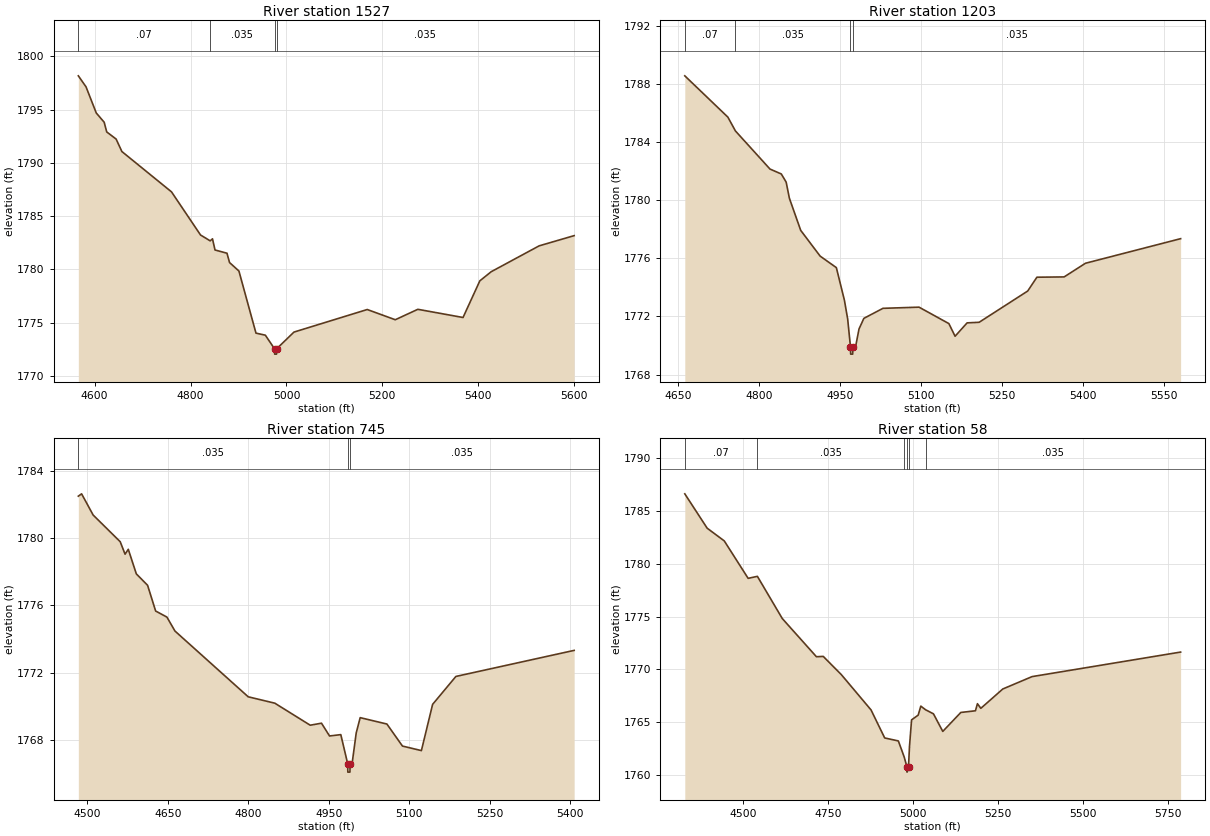
Type RM Length L Ch R = 1,1527,324,324,324
BEGIN DESCRIPTION:
Mapping XS b4401b97
END DESCRIPTION:
XS GIS Cut Line= 3
      1661509.99      6934223.88      1661916.23      6934376.65
      1662468.32      6934611.03
#Sta/Elev= 30
  4566.1 1798.18  4582.1 1797.15  4603.5 1794.69  4620.0 1793.82  4625.3 1792.91
  4644.9 1792.24  4656.9 1791.07  4760.4 1787.28  4820.9 1783.23  4841.0 1782.68
  4845.8 1782.87  4851.1 1781.82  4876.0 1781.52  4881.4 1780.64  4900.9 1779.85
  4936.5 1774.01  4956.0 1773.82  4975.2 1772.54  4975.5 1772.04  4979.3 1772.04
  4979.6 1772.54  5015.7 1774.11  5168.5 1776.23  5226.9 1775.27  5274.0 1776.25
  5368.2 1775.48  5403.2 1778.92  5426.9 1779.78  5526.9 1782.21  5599.9 1783.17
#Mann=4,-1,0
  4566.1    0.07       0  4841.0   0.035       0  4975.2   0.035       0
  4979.6   0.035       0
Bank Sta=4975.2,4979.6
Exp/Cntr=0.3,0.1

Type RM Length L Ch R = 1,1203,458,458,458
BEGIN DESCRIPTION:
Mapping XS 528af82d
END DESCRIPTION:
XS GIS Cut Line= 3
      1661388.44      6934385.32      1661669.70      6934574.57
      1662190.27      6934829.64
#Sta/Elev= 30
  4662.1 1788.55  4741.9 1785.71  4755.9 1784.76  4819.9 1782.14  4840.9 1781.80
  4849.9 1781.24  4855.9 1780.13  4876.9 1777.92  4912.9 1776.15  4942.9 1775.36
  4957.9 1773.11  4963.9 1771.82  4969.1 1769.91  4969.4 1769.41  4973.2 1769.41
  4973.5 1769.91  4978.9 1769.99  4984.9 1771.14  4993.9 1771.87  5029.3 1772.56
  5096.1 1772.64  5151.4 1771.51  5162.9 1770.64  5185.2 1771.56  5207.5 1771.60
  5297.5 1773.75  5314.5 1774.70  5365.0 1774.72  5404.5 1775.66  5580.8 1777.35
#Mann=4,-1,0
  4662.1    0.07       0  4755.9   0.035       0  4969.1   0.035       0
  4973.5   0.035       0
Bank Sta=4969.1,4973.5
Exp/Cntr=0.3,0.1

Type RM Length L Ch R = 1,745,687,687,687
BEGIN DESCRIPTION:
Mapping XS 73916e40
END DESCRIPTION:
XS GIS Cut Line= 3
      1661308.56      6934505.08      1661598.52      6934937.41
      1661845.06      6935256.88
#Sta/Elev= 30
  4483.0 1782.49  4489.1 1782.63  4510.6 1781.37  4561.1 1779.78  4570.1 1779.04
  4576.1 1779.33  4591.1 1777.87  4612.1 1777.19  4627.1 1775.66  4648.1 1775.30
  4663.1 1774.47  4799.6 1770.56  4849.2 1770.18  4915.2 1768.87  4936.2 1768.99
  4951.2 1768.23  4972.2 1768.31  4985.0 1766.58  4985.3 1766.08  4989.2 1766.08
  4989.5 1766.58  4993.3 1766.60  5000.9 1768.41  5008.3 1769.32  5058.1 1768.94
  5087.1 1767.63  5122.4 1767.36  5143.3 1770.11  5186.7 1771.77  5407.1 1773.32
#Mann=3,-1,0
  4483.0   0.035       0  4985.0   0.035       0  4989.5   0.035       0
Bank Sta=4985,4989.5
Exp/Cntr=0.3,0.1

Type RM Length L Ch R = 1,58,0,0,0
BEGIN DESCRIPTION:
Chimney Creek 1100 2.0
END DESCRIPTION:
XS GIS Cut Line= 3
      1660994.35      6934312.39      1661061.24      6934980.25
      1661744.41      6935373.95
#Sta/Elev= 30
  4328.8 1786.60  4394.7 1783.35  4445.0 1782.15  4515.3 1778.61  4542.5 1778.80
  4615.8 1774.81  4716.3 1771.20  4736.4 1771.23  4789.3 1769.52  4877.1 1766.17
  4917.3 1763.52  4957.5 1763.24  4974.5 1761.74  4982.8 1760.79  4983.1 1760.29
  4987.4 1760.79  4990.2 1762.67  4996.4 1765.23  5015.9 1765.68  5023.6 1766.53
  5037.5 1766.19  5060.9 1765.80  5088.3 1764.14  5141.4 1765.93  5184.5 1766.09
  5190.3 1766.76  5200.3 1766.32  5265.0 1768.15  5351.2 1769.32  5788.5 1771.64
#Mann=6,-1,0
  4328.8    0.07       0  4542.5   0.035       0  4974.5    0.07       0
  4982.8    0.07       0  4987.4    0.07       0  5037.5   0.035       0
Bank Sta=4982.8,4987.4
Exp/Cntr=0.3,0.1

Chan Stop Cuts=-1