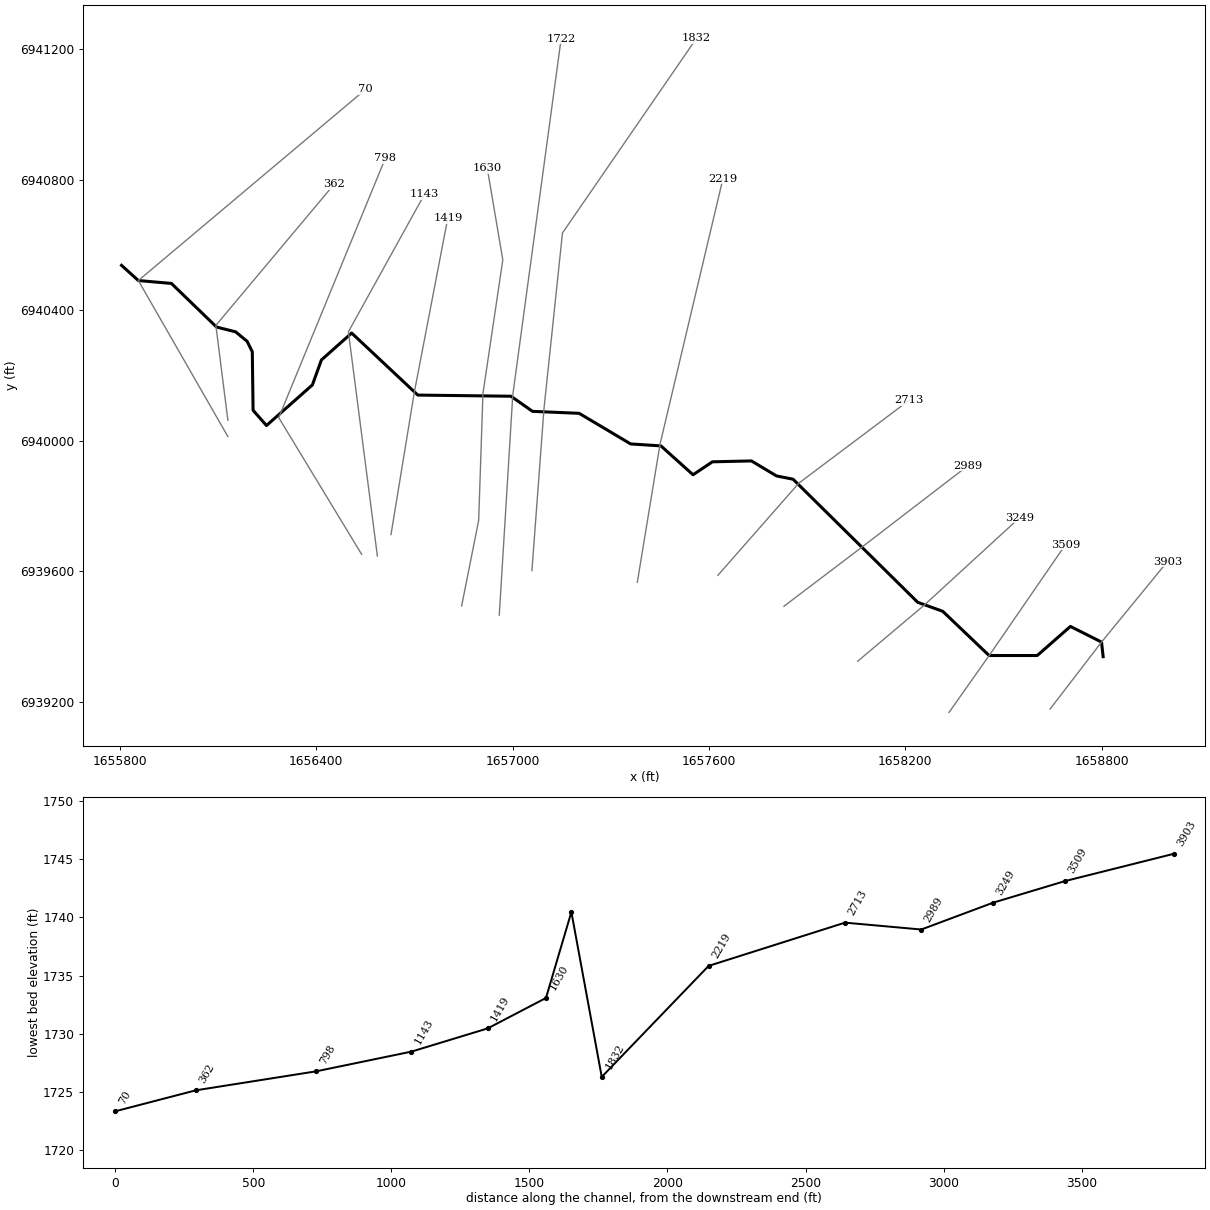
--- Chimney Creek 1101.prj (project) ---

Proj Title=Chimney Creek 1101 Base Level Engineering
Current Plan=p01
Default Exp/Contr=0.3,0.1
English Units
Geom File=g01
Flow File=f01
Plan File=p01
BEGIN DESCRIPTION:
Chimney Creek 1101
END DESCRIPTION:

--- Chimney Creek 1101.p01 (plan) ---

Plan Title=Multiple Run
Short Identifier=Multiple
Geom File=g01
Flow File=f01
Subcritical Flow
K Sum by GR= 0
Std Step Tol= 0.01
Critical Tol= 0.01
Num of Std Step Trials= 20
Max Error Tol= 0.3
Flow Tol Ratio= 0.001
Split Flow NTrial= 30
Split Flow Tol= 0.02
Split Flow Ratio= 0.02
Log Output Level= 0
Friction Slope Method= 1
Unsteady Friction Slope Method= 2
Unsteady Bridges Friction Slope Method= 1
Parabolic Critical Depth
Global Vel Dist=  1 , 1 , 1
Global Log Level= 0
CheckData=True
Encroach Param= -1, 0, 0, 0
BEGIN DESCRIPTION:
Multiple Run
END DESCRIPTION:

--- Chimney Creek 1101.f01 (steady flow) ---

Flow Title=Multiple
Number of Profiles=7
Profile Names=10-year,25-year,50-year,1pct_min,100-year,1pct_plu,500-year
River Rch & RM= Chimney Creek 11,Reach-1,3903
     231     318     389     237     473     944     710
River Rch & RM= Chimney Creek 11,Reach-1,1832
     287     400     494     303     605    1208     922
Boundary for River Rch & Prof#=Chimney Creek 11,Reach-1,1
Up Type=0
Dn Type=3
Dn Slope=0.005
Boundary for River Rch & Prof#=Chimney Creek 11,Reach-1,2
Up Type=0
Dn Type=3
Dn Slope=0.005
Boundary for River Rch & Prof#=Chimney Creek 11,Reach-1,3
Up Type=0
Dn Type=3
Dn Slope=0.005
Boundary for River Rch & Prof#=Chimney Creek 11,Reach-1,4
Up Type=0
Dn Type=3
Dn Slope=0.005
Boundary for River Rch & Prof#=Chimney Creek 11,Reach-1,5
Up Type=0
Dn Type=3
Dn Slope=0.005
Boundary for River Rch & Prof#=Chimney Creek 11,Reach-1,6
Up Type=0
Dn Type=3
Dn Slope=0.005
Boundary for River Rch & Prof#=Chimney Creek 11,Reach-1,7
Up Type=0
Dn Type=3
Dn Slope=0.005

--- Chimney Creek 1101.g01 (geometry) ---

Geom Title=Existing Conditions

River Reach=Chimney Creek 11,Reach-1
Reach XY= 30
      1658805.00      6939338.00      1658800.08      6939382.77
      1658704.94      6939430.75      1658603.53      6939341.55
      1658456.47      6939341.53      1658314.68      6939477.22
      1658238.33      6939504.65      1657857.30      6939882.17
      1657806.75      6939892.22      1657730.08      6939938.24
      1657610.86      6939935.54      1657551.59      6939895.81
      1657453.50      6939984.36      1657360.97      6939990.33
      1657203.44      6940084.24      1657060.94      6940090.27
      1656995.34      6940136.62      1656710.44      6940140.17
      1656508.32      6940330.42      1656415.78      6940247.72
      1656388.35      6940171.33      1656248.00      6940046.82
      1656207.06      6940093.44      1656204.67      6940272.97
      1656188.73      6940305.14      1656153.60      6940334.13
      1656095.34      6940348.79      1655957.44      6940482.50
      1655856.41      6940491.39      1655805.00      6940538.00

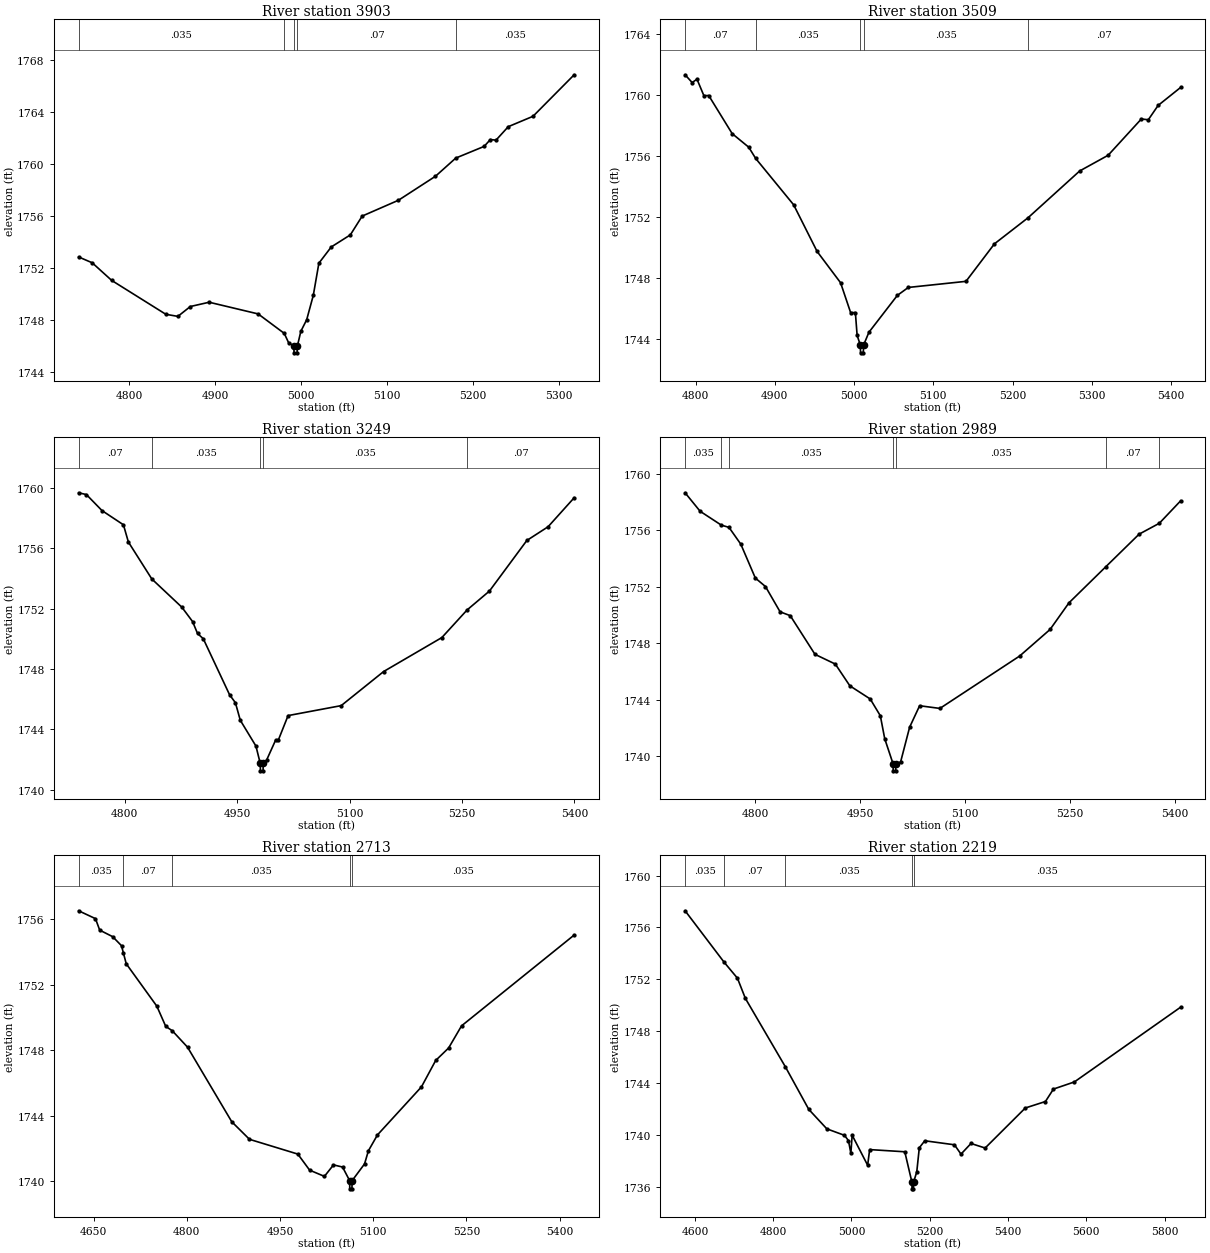
Type RM Length L Ch R = 1,3903,394,394,394
BEGIN DESCRIPTION:
Chimney Creek 1101 5.0
END DESCRIPTION:
XS GIS Cut Line= 3
      1658642.76      6939177.40      1658800.08      6939382.77
      1659001.06      6939629.21
#Sta/Elev= 30
  4741.3 1752.83  4757.1 1752.38  4779.8 1751.02  4842.8 1748.41  4856.8 1748.25
  4871.3 1749.01  4893.2 1749.34  4950.2 1748.44  4980.6 1746.94  4985.6 1746.23
  4991.8 1745.94  4992.0 1745.44  4995.5 1745.44  4995.8 1745.94  4999.9 1747.10
  5006.7 1747.99  5014.4 1749.87  5020.9 1752.35  5035.3 1753.60  5057.5 1754.53
  5071.3 1755.98  5113.5 1757.20  5156.6 1759.05  5180.2 1760.45  5213.2 1761.35
  5220.5 1761.88  5227.0 1761.83  5241.3 1762.87  5270.1 1763.67  5318.0 1766.87
#Mann=5,-1,0
  4741.3   0.035       0  4980.6    0.07       0  4991.8    0.07       0
  4995.8    0.07       0  5180.2   0.035       0
Bank Sta=4991.8,4995.8
Exp/Cntr=0.3,0.1

Type RM Length L Ch R = 1,3509,260,260,260
BEGIN DESCRIPTION:
Mapping XS a0125a12
END DESCRIPTION:
XS GIS Cut Line= 3
      1658333.90      6939167.13      1658457.59      6939342.89
      1658689.77      6939681.40
#Sta/Elev= 30
  4786.8 1761.34  4795.7 1760.83  4801.8 1761.05  4810.5 1759.97  4816.6 1759.98
  4846.2 1757.48  4867.1 1756.59  4875.9 1755.85  4923.8 1752.81  4953.4 1749.75
  4983.0 1747.70  4995.7 1745.74  5001.7 1745.74  5003.9 1744.25  5008.0 1743.60
  5008.2 1743.10  5011.7 1743.10  5012.0 1743.60  5018.8 1744.45  5054.7 1746.87
  5068.5 1747.39  5141.3 1747.79  5177.2 1750.25  5219.6 1751.96  5284.8 1755.03
  5320.7 1756.06  5362.6 1758.44  5371.4 1758.39  5383.8 1759.33  5412.2 1760.51
#Mann=5,-1,0
  4786.8    0.07       0  4875.9   0.035       0  5008.0   0.035       0
  5012.0   0.035       0  5219.6    0.07       0
Bank Sta=5008,5012
Exp/Cntr=0.3,0.1

Type RM Length L Ch R = 1,3249,260,260,260
BEGIN DESCRIPTION:
Mapping XS bb8ab374
END DESCRIPTION:
XS GIS Cut Line= 3
      1658054.79      6939324.00      1658256.63      6939494.59
      1658548.96      6939763.53
#Sta/Elev= 30
  4738.3 1759.67  4748.7 1759.55  4769.5 1758.49  4798.1 1757.55  4804.7 1756.41
  4836.0 1753.96  4876.1 1752.09  4890.4 1751.14  4897.0 1750.35  4904.7 1750.00
  4939.8 1746.29  4947.6 1745.76  4954.1 1744.60  4975.0 1742.89  4980.7 1741.75
  4981.0 1741.25  4984.5 1741.25  4984.7 1741.75  4989.3 1741.97  5001.3 1743.29
  5004.9 1743.29  5017.9 1744.91  5088.8 1745.57  5145.5 1747.83  5223.2 1750.08
  5256.9 1751.91  5286.7 1753.16  5336.6 1756.51  5365.0 1757.42  5399.8 1759.34
#Mann=5,-1,0
  4738.3    0.07       0  4836.0   0.035       0  4980.7   0.035       0
  4984.7   0.035       0  5256.9    0.07       0
Bank Sta=4980.7,4984.7
Exp/Cntr=0.3,0.1

Type RM Length L Ch R = 1,2989,276,276,276
BEGIN DESCRIPTION:
Mapping XS 60946bcd
END DESCRIPTION:
XS GIS Cut Line= 3
      1657829.47      6939492.55      1658069.03      6939674.82
      1658392.04      6939923.89
#Sta/Elev= 30
  4699.6 1758.64  4721.1 1757.33  4751.4 1756.35  4762.4 1756.19  4779.3 1755.00
  4800.1 1752.60  4814.6 1752.00  4835.5 1750.21  4850.0 1749.94  4885.4 1747.20
  4914.5 1746.51  4935.3 1744.97  4964.4 1744.04  4978.9 1742.85  4985.2 1741.22
  4997.1 1739.45  4997.4 1738.95  5000.9 1738.95  5001.1 1739.45  5007.9 1739.58
  5020.8 1742.04  5035.1 1743.56  5064.1 1743.37  5178.2 1747.08  5221.7 1748.96
  5248.8 1750.85  5301.4 1753.40  5349.1 1755.71  5378.0 1756.48  5408.5 1758.07
#Mann=7,-1,0
  4699.6   0.035       0  4751.4    0.07       0  4762.4   0.035       0
  4997.1   0.035       0  5001.1   0.035       0  5301.4    0.07       0
  5378.0   0.035       0
Bank Sta=4997.1,5001.1
Exp/Cntr=0.3,0.1

Type RM Length L Ch R = 1,2713,494,494,494
BEGIN DESCRIPTION:
Mapping XS a95222c3
END DESCRIPTION:
XS GIS Cut Line= 3
      1657627.62      6939587.58      1657875.01      6939870.13
      1658212.03      6940124.18
#Sta/Elev= 30
  4625.8 1756.50  4652.9 1756.02  4659.7 1755.32  4680.6 1754.92  4694.8 1754.37
  4697.7 1753.95  4702.4 1753.27  4751.7 1750.68  4766.0 1749.45  4776.6 1749.18
  4801.1 1748.18  4872.3 1743.63  4900.8 1742.56  4978.6 1741.66  4997.6 1740.68
  5021.4 1740.30  5036.0 1741.00  5050.6 1740.87  5062.0 1740.04  5062.2 1739.54
  5065.7 1739.54  5066.0 1740.04  5086.0 1741.06  5092.2 1741.86  5106.8 1742.83
  5177.6 1745.76  5200.5 1747.37  5221.3 1748.13  5242.1 1749.48  5423.4 1755.02
#Mann=5,-1,0
  4625.8   0.035       0  4697.7    0.07       0  4776.6   0.035       0
  5062.0   0.035       0  5066.0   0.035       0
Bank Sta=5062,5066
Exp/Cntr=0.3,0.1

Type RM Length L Ch R = 1,2219,387,387,387
BEGIN DESCRIPTION:
Mapping XS 21a1e6e5
END DESCRIPTION:
XS GIS Cut Line= 3
      1657381.32      6939566.03      1657450.75      6939989.59
      1657643.15      6940804.26
#Sta/Elev= 30
  4574.9 1757.29  4674.6 1753.32  4708.6 1752.09  4728.9 1750.53  4831.1 1745.25
  4891.0 1741.96  4937.1 1740.46  4982.2 1739.96  4992.4 1739.55  4998.5 1738.57
  5001.8 1739.97  5041.4 1737.65  5046.5 1738.86  5136.3 1738.69  5154.6 1736.33
  5154.9 1735.83  5158.4 1735.83  5158.6 1736.33  5166.9 1737.14  5173.4 1739.00
  5187.4 1739.54  5263.2 1739.23  5279.9 1738.51  5305.5 1739.33  5341.6 1738.98
  5444.3 1742.07  5495.7 1742.57  5516.2 1743.53  5569.6 1744.08  5841.2 1749.85
#Mann=5,-1,0
  4574.9   0.035       0  4674.6    0.07       0  4831.1   0.035       0
  5154.6   0.035       0  5158.6   0.035       0
Bank Sta=5154.6,5158.6
Exp/Cntr=0.3,0.1

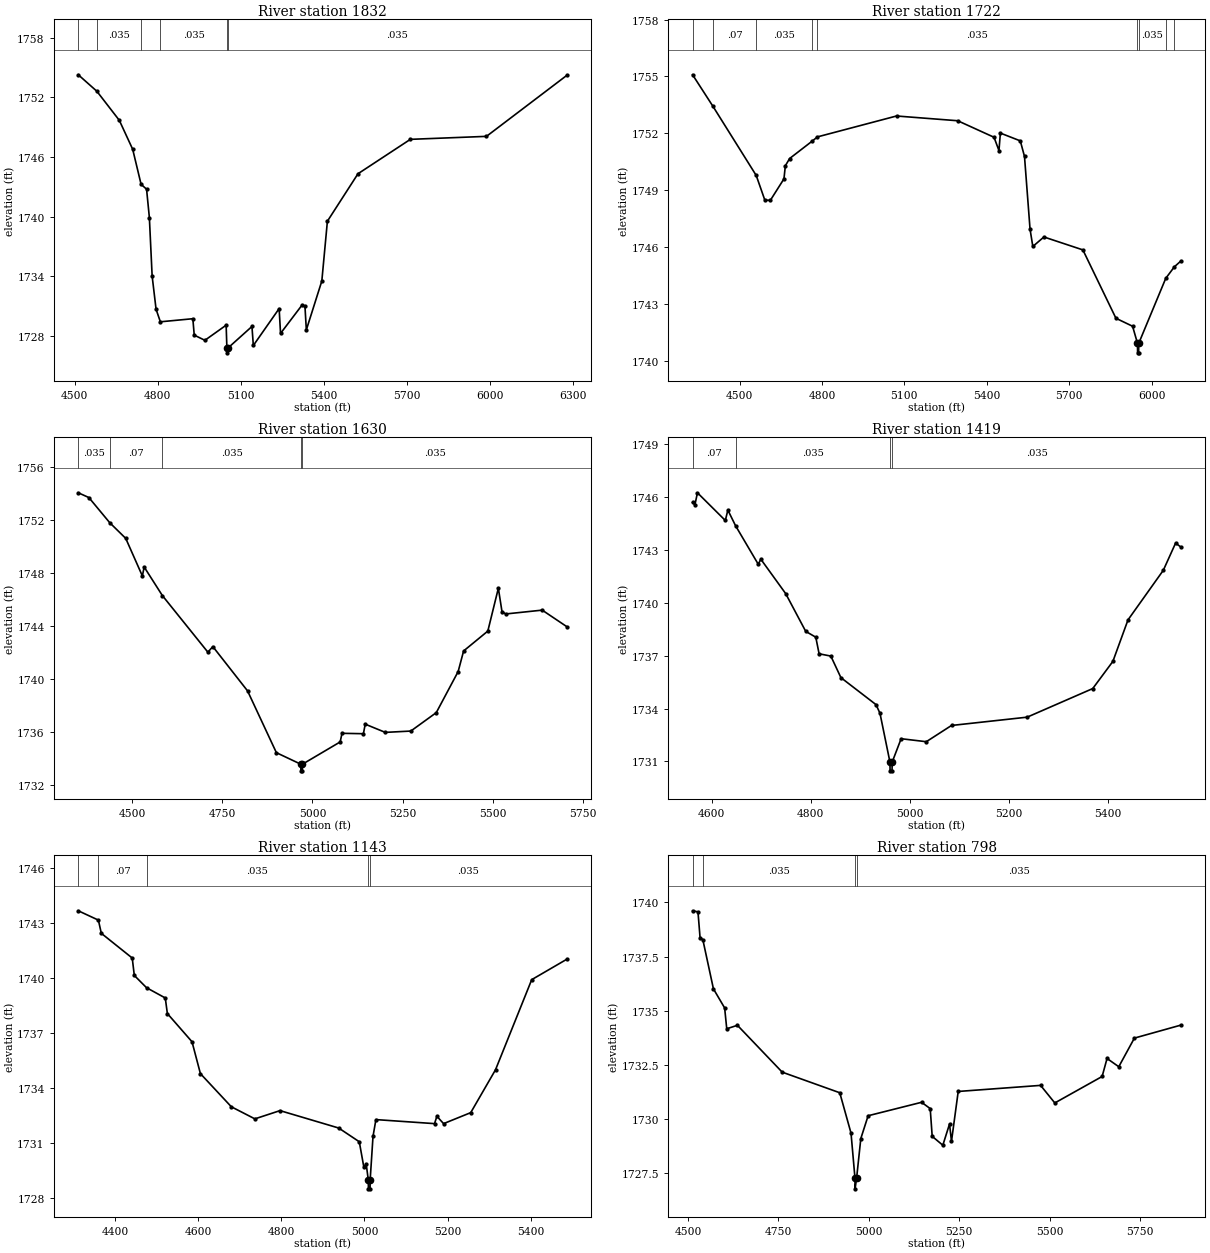
Type RM Length L Ch R = 1,1832,110,110,110
BEGIN DESCRIPTION:
Mapping XS 2ed8a928
END DESCRIPTION:
XS GIS Cut Line= 4
      1657059.26      6939602.04      1657096.15      6940098.99
      1657152.58      6940637.19      1657562.20      6941234.21
#Sta/Elev= 30
  4513.1 1754.26  4580.0 1752.61  4661.3 1749.68  4709.6 1746.77  4739.9 1743.25
  4759.7 1742.76  4769.8 1739.91  4779.8 1734.03  4794.0 1730.69  4809.5 1729.43
  4926.8 1729.74  4931.8 1728.09  4970.3 1727.57  5047.0 1729.09  5049.7 1726.81
  5050.0 1726.31  5054.2 1726.81  5140.2 1728.96  5145.2 1727.05  5238.4 1730.76
  5243.4 1728.26  5322.1 1731.15  5331.6 1730.98  5336.6 1728.62  5392.5 1733.53
  5412.6 1739.54  5523.0 1744.31  5712.2 1747.77  5987.0 1748.07  6276.6 1754.19
#Mann=6,-1,0
  4513.1    0.07       0  4580.0   0.035       0  4739.9    0.07       0
  4809.5   0.035       0  5049.7   0.035       0  5054.2   0.035       0
Bank Sta=5049.7,5054.2
Exp/Cntr=0.3,0.1

Type RM Length L Ch R = 1,1722,92,92,92
BEGIN DESCRIPTION:
Mapping XS 37206c92
END DESCRIPTION:
XS GIS Cut Line= 3
      1656959.44      6939465.35      1657000.67      6940140.23
      1657148.51      6941232.74
#Sta/Elev= 30
  4328.8 1755.09  4402.0 1753.45  4560.5 1749.79  4591.9 1748.49  4612.0 1748.48
  4661.5 1749.61  4666.6 1750.30  4682.1 1750.68  4764.6 1751.60  4783.5 1751.82
  5071.4 1752.92  5294.3 1752.67  5426.5 1751.80  5444.5 1751.10  5449.6 1752.02
  5522.2 1751.61  5537.5 1750.79  5557.7 1746.96  5567.8 1746.05  5608.2 1746.55
  5750.1 1745.87  5870.5 1742.27  5931.1 1741.85  5949.0 1740.95  5949.3 1740.45
  5953.2 1740.45  5953.5 1740.95  6051.8 1744.37  6083.3 1744.98  6107.4 1745.29
#Mann=9,-1,0
  4328.8   0.035       0  4402.0    0.07       0  4560.5   0.035       0
  4764.6    0.07       0  4783.5   0.035       0  5949.0   0.035       0
  5953.5   0.035       0  6051.8    0.07       0  6083.3   0.035       0
Bank Sta=5949,5953.5
Exp/Cntr=0.3,0.1

Type RM Length L Ch R = 1,1630,211,211,211
BEGIN DESCRIPTION:
Mapping XS 101b3ca6
END DESCRIPTION:
XS GIS Cut Line= 5
      1656844.42      6939493.53      1656896.50      6939756.11
      1656909.52      6940144.57      1656970.28      6940554.72
      1656922.86      6940834.94
#Sta/Elev= 30
  4350.1 1754.05  4379.5 1753.69  4437.5 1751.79  4481.8 1750.61  4527.9 1747.78
  4533.0 1748.45  4583.4 1746.30  4709.7 1742.03  4723.5 1742.45  4819.8 1739.11
  4899.8 1734.45  4967.6 1733.58  4967.9 1733.08  4971.8 1733.08  4972.1 1733.58
  5076.8 1735.26  5081.9 1735.91  5141.3 1735.88  5146.3 1736.60  5202.0 1735.98
  5272.8 1736.08  5343.5 1737.47  5404.2 1740.57  5419.3 1742.12  5486.5 1743.62
  5515.7 1746.85  5525.8 1745.09  5536.0 1744.91  5637.4 1745.20  5705.3 1743.96
#Mann=5,-1,0
  4350.1   0.035       0  4437.5    0.07       0  4583.4   0.035       0
  4967.6   0.035       0  4972.1   0.035       0
Bank Sta=4967.6,4972.1
Exp/Cntr=0.3,0.1

Type RM Length L Ch R = 1,1419,276,276,276
BEGIN DESCRIPTION:
Mapping XS 4af3093e
END DESCRIPTION:
XS GIS Cut Line= 3
      1656628.55      6939712.55      1656699.74      6940148.36
      1656802.17      6940683.06
#Sta/Elev= 30
  4561.3 1745.67  4566.0 1745.54  4571.1 1746.22  4627.4 1744.65  4632.5 1745.24
  4648.1 1744.35  4693.9 1742.17  4699.0 1742.46  4749.2 1740.51  4789.7 1738.37
  4810.0 1738.04  4816.7 1737.10  4840.4 1736.97  4860.7 1735.75  4931.6 1734.22
  4939.6 1733.73  4959.7 1730.97  4960.0 1730.47  4963.9 1730.47  4964.3 1730.97
  4982.3 1732.29  5033.1 1732.12  5084.0 1733.04  5236.7 1733.51  5369.1 1735.13
  5409.8 1736.67  5440.3 1739.02  5511.6 1741.83  5536.4 1743.37  5547.3 1743.14
#Mann=4,-1,0
  4561.3    0.07       0  4648.1   0.035       0  4959.7   0.035       0
  4964.3   0.035       0
Bank Sta=4959.7,4964.3
Exp/Cntr=0.3,0.1

Type RM Length L Ch R = 1,1143,345,345,345
BEGIN DESCRIPTION:
Mapping XS e423fe0e
END DESCRIPTION:
XS GIS Cut Line= 3
      1656586.89      6939646.66      1656498.35      6940334.12
      1656730.99      6940755.99
#Sta/Elev= 30
  4311.7 1743.66  4360.1 1743.15  4367.1 1742.43  4441.5 1741.08  4446.5 1740.13
  4475.9 1739.46  4521.0 1738.90  4526.0 1738.05  4585.3 1736.51  4605.5 1734.77
  4679.9 1732.96  4736.5 1732.30  4797.0 1732.75  4938.2 1731.80  4987.7 1731.05
  4998.7 1729.66  5004.3 1729.84  5009.3 1728.98  5009.7 1728.48  5013.6 1728.48
  5013.9 1728.98  5020.7 1731.34  5027.7 1732.26  5168.7 1732.04  5174.4 1732.44
  5190.5 1732.04  5255.8 1732.64  5315.4 1734.98  5402.5 1739.90  5486.6 1741.01
#Mann=5,-1,0
  4311.7   0.035       0  4360.1    0.07       0  4475.9   0.035       0
  5009.3   0.035       0  5013.9   0.035       0
Bank Sta=5009.3,5013.9
Exp/Cntr=0.3,0.1

Type RM Length L Ch R = 1,798,436,436,436
BEGIN DESCRIPTION:
Mapping XS d1248777
END DESCRIPTION:
XS GIS Cut Line= 3
      1656538.70      6939651.95      1656285.47      6940070.97
      1656611.62      6940867.17
#Sta/Elev= 30
  4512.9 1739.61  4527.8 1739.56  4533.6 1738.36  4541.2 1738.28  4570.5 1736.01
  4601.5 1735.13  4607.3 1734.17  4636.8 1734.33  4760.6 1732.17  4919.7 1731.22
  4950.8 1729.36  4961.7 1727.29  4962.0 1726.79  4966.3 1727.29  4977.9 1729.11
  4998.1 1730.16  5145.8 1730.78  5169.7 1730.49  5175.2 1729.21  5204.6 1728.80
  5223.1 1729.78  5228.5 1728.98  5247.1 1731.28  5474.8 1731.56  5514.1 1730.75
  5644.9 1731.97  5658.5 1732.80  5690.9 1732.42  5734.1 1733.74  5862.9 1734.34
#Mann=4,-1,0
  4512.9    0.07       0  4541.2   0.035       0  4961.7   0.035       0
  4966.3   0.035       0
Bank Sta=4961.7,4966.3
Exp/Cntr=0.3,0.1

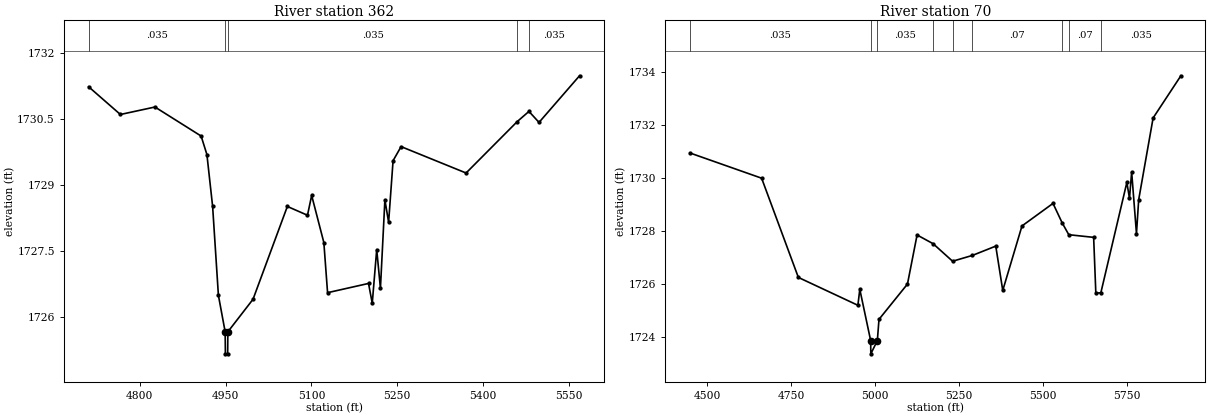
Type RM Length L Ch R = 1,362,292,292,292
BEGIN DESCRIPTION:
Mapping XS ff77573f
END DESCRIPTION:
XS GIS Cut Line= 3
      1656130.00      6940062.96      1656093.35      6940353.96
      1656455.38      6940787.34
#Sta/Elev= 30
  4710.7 1731.23  4766.2 1730.60  4826.6 1730.77  4907.3 1730.11  4917.4 1729.69
  4927.4 1728.51  4937.5 1726.49  4949.3 1725.66  4949.7 1725.16  4953.7 1725.16
  4954.0 1725.66  4998.0 1726.40  5058.0 1728.51  5093.2 1728.31  5100.5 1728.76
  5121.8 1727.69  5128.3 1726.55  5199.9 1726.76  5206.4 1726.31  5214.2 1727.53
  5220.7 1726.65  5228.5 1728.66  5235.0 1728.15  5242.8 1729.55  5256.8 1729.87
  5370.4 1729.27  5459.9 1730.44  5480.3 1730.67  5497.9 1730.42  5568.7 1731.48
#Mann=5,-1,0
  4710.7   0.035       0  4949.3   0.035       0  4954.0   0.035       0
  5459.9    0.07       0  5480.3   0.035       0
Bank Sta=4949.3,4954
Exp/Cntr=0.3,0.1

Type RM Length L Ch R = 1,70,0,0,0
BEGIN DESCRIPTION:
Chimney Creek 1101 1.0
END DESCRIPTION:
XS GIS Cut Line= 3
      1656130.00      6940013.00      1655856.41      6940491.39
      1656551.28      6941077.89
#Sta/Elev= 30
  4448.9 1730.93  4662.0 1729.98  4771.3 1726.24  4948.4 1725.19  4954.1 1725.79
  4986.4 1723.86  4986.9 1723.36  5006.3 1723.86  5011.2 1724.66  5095.9 1725.99
  5124.5 1727.84  5172.3 1727.51  5230.2 1726.85  5289.2 1727.07  5358.6 1727.42
  5379.4 1725.75  5436.6 1728.18  5528.9 1729.03  5556.0 1728.30  5575.8 1727.85
  5649.8 1727.75  5656.3 1725.65  5671.2 1725.66  5748.6 1729.82  5756.4 1729.22
  5762.9 1730.21  5777.2 1727.89  5783.8 1729.17  5826.7 1732.25  5909.3 1733.84
#Mann=9,-1,0
  4448.9   0.035       0  4986.4   0.035       0  5006.3   0.035       0
  5172.3    0.07       0  5230.2   0.035       0  5289.2    0.07       0
  5556.0   0.035       0  5575.8    0.07       0  5671.2   0.035       0
Bank Sta=4986.4,5006.3
Exp/Cntr=0.3,0.1

Chan Stop Cuts=-1