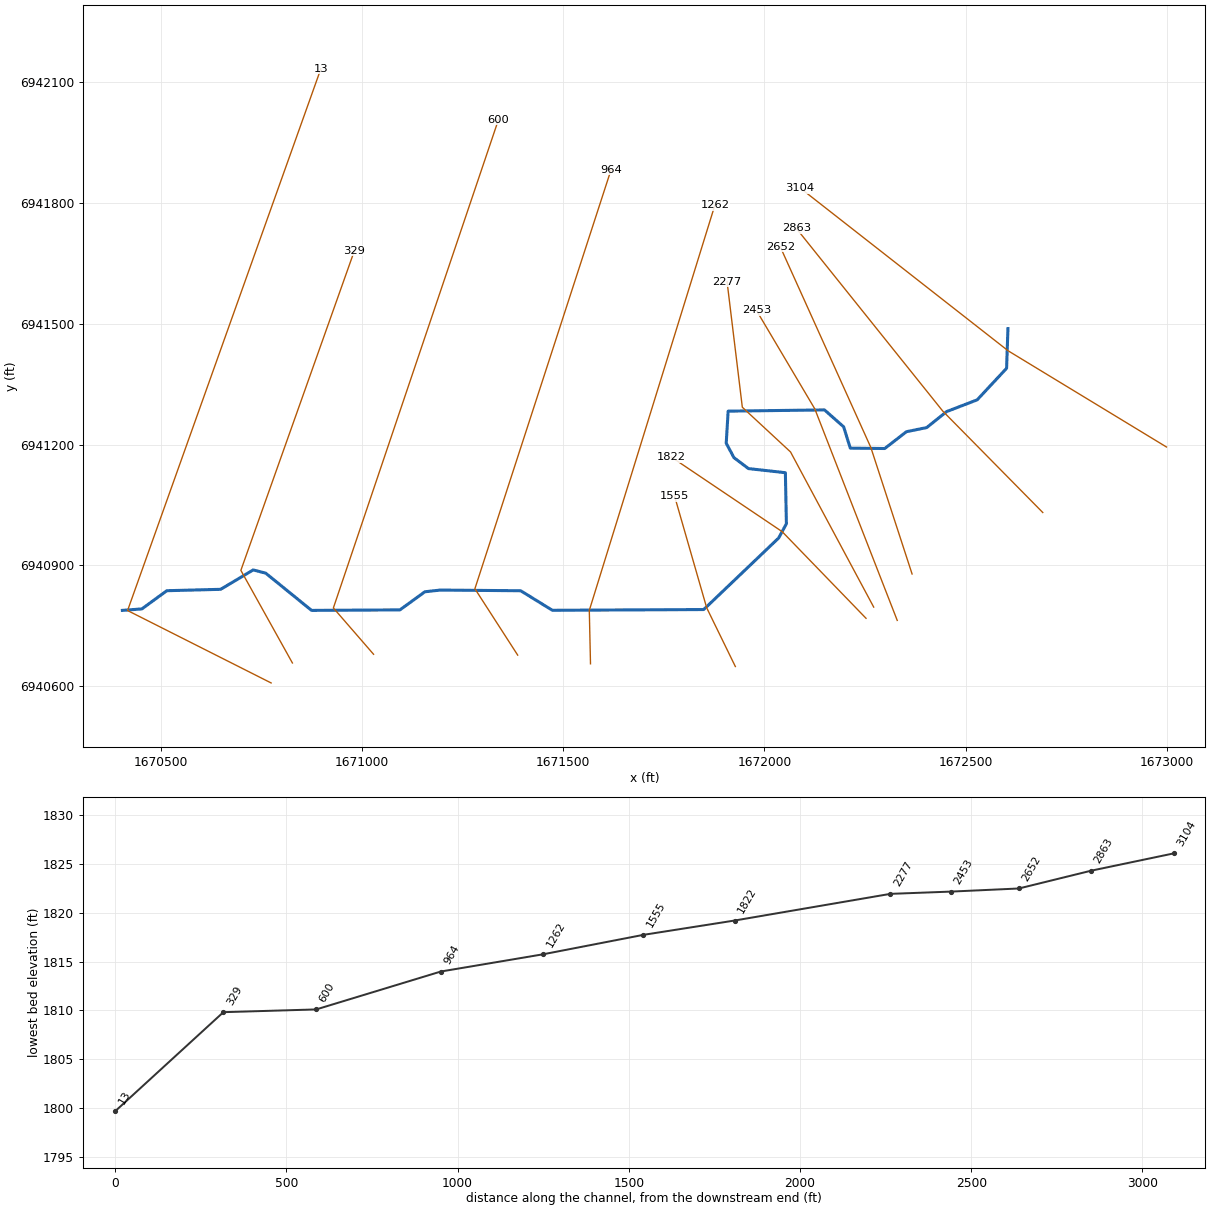
--- Chimney Creek 1103.prj (project) ---

Proj Title=Chimney Creek 1103 Base Level Engineering
Current Plan=p01
Default Exp/Contr=0.3,0.1
English Units
Geom File=g01
Flow File=f01
Plan File=p01
BEGIN DESCRIPTION:
Chimney Creek 1103
END DESCRIPTION:

--- Chimney Creek 1103.p01 (plan) ---

Plan Title=Multiple Run
Short Identifier=Multiple
Geom File=g01
Flow File=f01
Subcritical Flow
K Sum by GR= 0
Std Step Tol= 0.01
Critical Tol= 0.01
Num of Std Step Trials= 20
Max Error Tol= 0.3
Flow Tol Ratio= 0.001
Split Flow NTrial= 30
Split Flow Tol= 0.02
Split Flow Ratio= 0.02
Log Output Level= 0
Friction Slope Method= 1
Unsteady Friction Slope Method= 2
Unsteady Bridges Friction Slope Method= 1
Parabolic Critical Depth
Global Vel Dist=  1 , 1 , 1
Global Log Level= 0
CheckData=True
Encroach Param= -1, 0, 0, 0
BEGIN DESCRIPTION:
Multiple Run
END DESCRIPTION:

--- Chimney Creek 1103.f01 (steady flow) ---

Flow Title=Multiple
Number of Profiles=7
Profile Names=10-year,25-year,50-year,1pct_min,100-year,1pct_plu,500-year
River Rch & RM= Chimney Creek 11,Reach-1,3104
     280     389     479     294     587    1171     891
River Rch & RM= Chimney Creek 11,Reach-1,13
     633     910    1147     717    1431    2856    2261
Boundary for River Rch & Prof#=Chimney Creek 11,Reach-1,1
Up Type=0
Dn Type=3
Dn Slope=0.005
Boundary for River Rch & Prof#=Chimney Creek 11,Reach-1,2
Up Type=0
Dn Type=3
Dn Slope=0.005
Boundary for River Rch & Prof#=Chimney Creek 11,Reach-1,3
Up Type=0
Dn Type=3
Dn Slope=0.005
Boundary for River Rch & Prof#=Chimney Creek 11,Reach-1,4
Up Type=0
Dn Type=3
Dn Slope=0.005
Boundary for River Rch & Prof#=Chimney Creek 11,Reach-1,5
Up Type=0
Dn Type=3
Dn Slope=0.005
Boundary for River Rch & Prof#=Chimney Creek 11,Reach-1,6
Up Type=0
Dn Type=3
Dn Slope=0.005
Boundary for River Rch & Prof#=Chimney Creek 11,Reach-1,7
Up Type=0
Dn Type=3
Dn Slope=0.005

--- Chimney Creek 1103.g01 (geometry) ---

Geom Title=Existing Conditions

River Reach=Chimney Creek 11,Reach-1
Reach XY= 30
      1672605.00      6941488.00      1672601.62      6941389.39
      1672528.52      6941310.98      1672452.82      6941281.90
      1672403.28      6941242.16      1672352.82      6941231.88
      1672298.95      6941190.10      1672213.35      6941191.00
      1672196.83      6941244.03      1672149.32      6941285.99
      1671909.92      6941282.96      1671905.12      6941203.22
      1671924.38      6941167.39      1671960.37      6941140.22
      1672052.07      6941130.02      1672054.64      6941003.18
      1672035.40      6940967.84      1671849.15      6940790.06
      1671473.27      6940788.21      1671394.50      6940836.78
      1671194.81      6940838.45      1671156.57      6940834.22
      1671094.50      6940789.22      1670874.98      6940787.96
      1670761.05      6940880.50      1670730.04      6940888.49
      1670649.07      6940840.30      1670515.47      6940836.87
      1670453.49      6940791.65      1670405.00      6940788.00

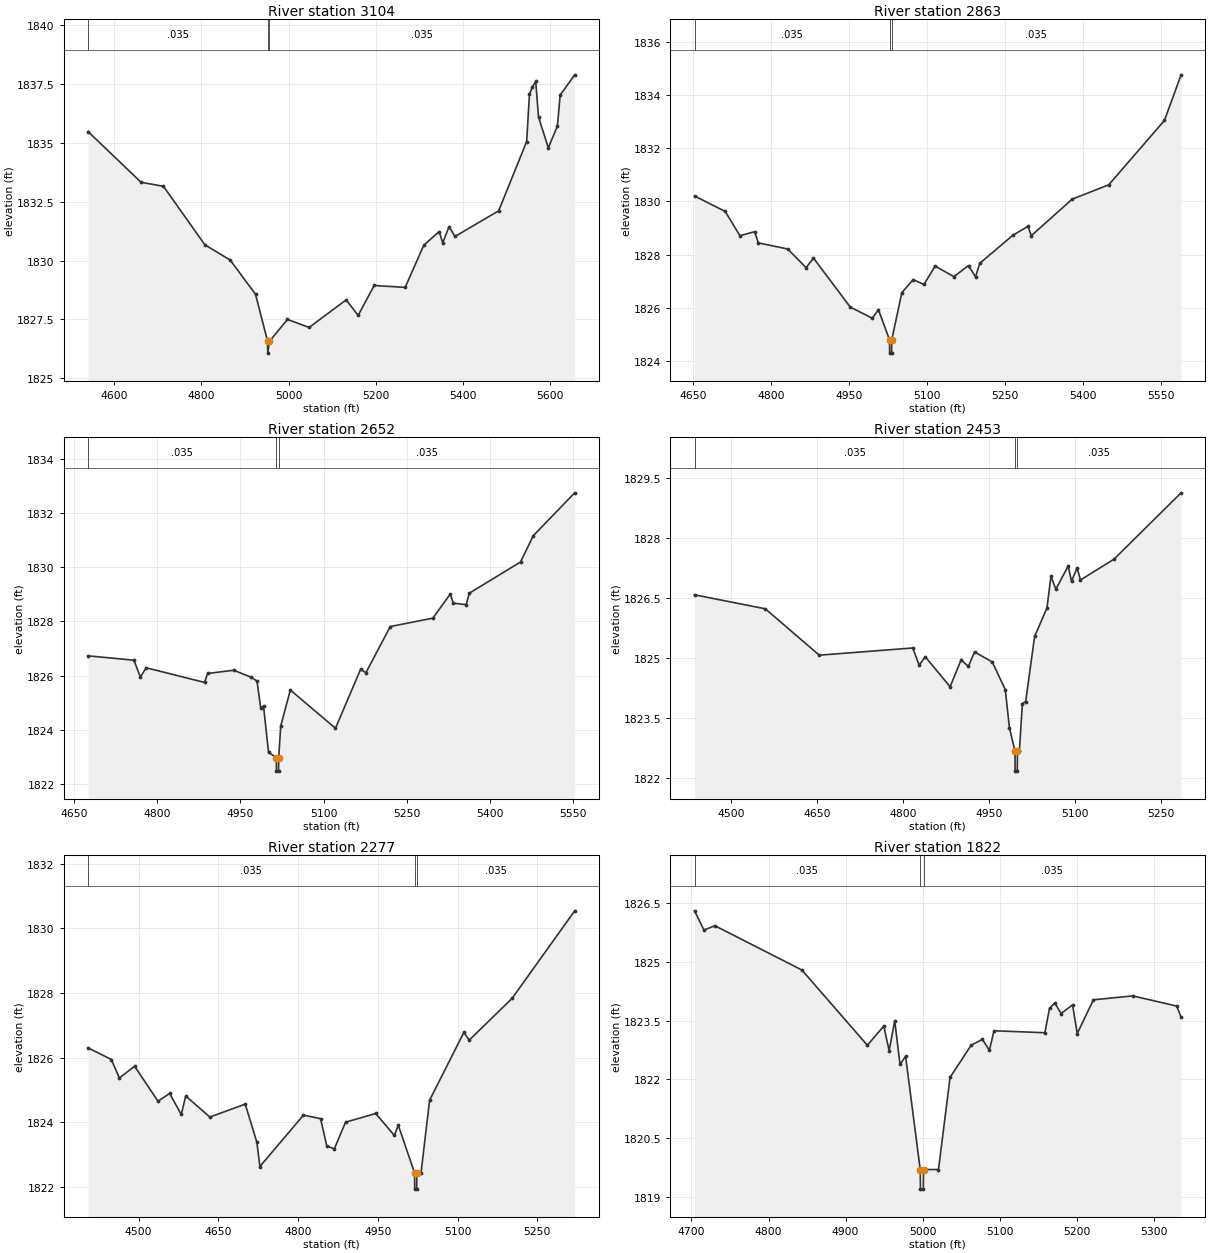
Type RM Length L Ch R = 1,3104,241,241,241
BEGIN DESCRIPTION:
Chimney Creek 1103 2.0
END DESCRIPTION:
XS GIS Cut Line= 3
      1672998.81      6941193.90      1672605.76      6941432.68
      1672088.70      6941837.37
#Sta/Elev= 30
  4540.1 1835.47  4661.6 1833.32  4713.0 1833.15  4807.9 1830.67  4866.1 1830.02
  4924.2 1828.57  4952.0 1826.57  4952.2 1826.07  4956.2 1826.57  4997.5 1827.50
  5047.3 1827.16  5132.3 1828.33  5159.7 1827.67  5196.5 1828.94  5267.6 1828.86
  5310.4 1830.65  5345.7 1831.23  5353.8 1830.75  5368.3 1831.44  5381.9 1831.02
  5482.2 1832.11  5546.4 1835.05  5552.8 1837.05  5559.7 1837.37  5567.2 1837.60
  5573.6 1836.09  5596.1 1834.78  5617.0 1835.71  5623.3 1837.02  5656.6 1837.88
#Mann=3,-1,0
  4540.1   0.035       0  4952.0   0.035       0  4956.2   0.035       0
Bank Sta=4952,4956.2
Exp/Cntr=0.3,0.1

Type RM Length L Ch R = 1,2863,211,211,211
BEGIN DESCRIPTION:
Mapping XS 9432e196
END DESCRIPTION:
XS GIS Cut Line= 3
      1672691.53      6941031.12      1672443.26      6941282.87
      1672079.31      6941736.94
#Sta/Elev= 30
  4652.6 1830.20  4711.6 1829.62  4739.9 1828.71  4768.2 1828.86  4775.2 1828.44
  4831.7 1828.21  4867.2 1827.51  4881.3 1827.87  4952.0 1826.03  4994.4 1825.61
  5006.2 1825.93  5027.5 1824.80  5027.8 1824.30  5031.5 1824.30  5031.8 1824.80
  5051.2 1826.57  5072.9 1827.06  5093.7 1826.88  5115.3 1827.57  5151.3 1827.17
  5179.4 1827.59  5192.9 1827.16  5200.9 1827.67  5264.9 1828.73  5293.7 1829.06
  5300.1 1828.71  5378.6 1830.08  5449.0 1830.62  5556.2 1833.04  5588.1 1834.75
#Mann=3,-1,0
  4652.6   0.035       0  5027.5   0.035       0  5031.8   0.035       0
Bank Sta=5027.5,5031.8
Exp/Cntr=0.3,0.1

Type RM Length L Ch R = 1,2652,199,199,199
BEGIN DESCRIPTION:
Mapping XS 0aa0dbbe
END DESCRIPTION:
XS GIS Cut Line= 3
      1672366.85      6940878.40      1672264.44      6941192.59
      1672039.38      6941691.19
#Sta/Elev= 30
  4675.3 1826.73  4757.9 1826.57  4769.5 1825.95  4780.1 1826.29  4885.2 1825.75
  4890.8 1826.08  4937.8 1826.20  4969.4 1825.94  4979.9 1825.80  4986.5 1824.82
  4991.7 1824.87  5000.7 1823.17  5014.7 1822.98  5015.0 1822.48  5018.7 1822.48
  5019.0 1822.98  5022.7 1824.15  5040.0 1825.47  5121.4 1824.06  5166.6 1826.23
  5176.3 1826.11  5220.2 1827.81  5297.0 1828.12  5328.5 1829.01  5333.9 1828.67
  5357.1 1828.62  5362.8 1829.04  5455.1 1830.19  5478.2 1831.16  5552.8 1832.74
#Mann=3,-1,0
  4675.3   0.035       0  5014.7   0.035       0  5019.0   0.035       0
Bank Sta=5014.7,5019
Exp/Cntr=0.3,0.1

Type RM Length L Ch R = 1,2453,176,176,176
BEGIN DESCRIPTION:
Mapping XS eda1eadc
END DESCRIPTION:
XS GIS Cut Line= 3
      1672329.99      6940763.04      1672125.24      6941288.45
      1671980.16      6941533.30
#Sta/Elev= 30
  4436.1 1826.57  4559.5 1826.22  4653.6 1825.06  4816.7 1825.24  4827.8 1824.81
  4838.5 1825.02  4881.8 1824.27  4900.9 1824.94  4913.7 1824.78  4924.4 1825.14
  4955.3 1824.89  4978.0 1824.20  4985.2 1823.25  4994.9 1822.66  4995.2 1822.16
  4998.9 1822.16  4999.2 1822.66  5002.6 1822.66  5007.8 1823.85  5013.6 1823.90
  5029.2 1825.53  5050.7 1826.24  5057.6 1827.03  5066.3 1826.71  5087.7 1827.29
  5093.5 1826.91  5103.3 1827.24  5109.1 1826.94  5167.6 1827.46  5284.6 1829.12
#Mann=3,-1,0
  4436.1   0.035       0  4994.9   0.035       0  4999.2   0.035       0
Bank Sta=4994.9,4999.2
Exp/Cntr=0.3,0.1

Type RM Length L Ch R = 1,2277,455,455,455
BEGIN DESCRIPTION:
Mapping XS 8a76306c
END DESCRIPTION:
XS GIS Cut Line= 4
      1672271.50      6940796.16      1672064.93      6941181.53
      1671945.14      6941292.64      1671907.18      6941604.91
#Sta/Elev= 30
  4405.2 1826.30  4448.9 1825.94  4464.0 1825.37  4492.7 1825.73  4536.6 1824.65
  4558.5 1824.89  4580.4 1824.24  4588.8 1824.81  4634.2 1824.16  4700.7 1824.56
  4722.6 1823.38  4728.3 1822.63  4810.3 1824.22  4842.4 1824.11  4854.2 1823.26
  4868.4 1823.18  4889.4 1824.00  4946.1 1824.27  4981.3 1823.59  4988.6 1823.91
  5019.2 1822.43  5019.5 1821.93  5023.2 1821.93  5023.5 1822.43  5031.4 1822.44
  5047.5 1824.68  5112.0 1826.78  5122.0 1826.54  5202.6 1827.83  5320.4 1830.54
#Mann=3,-1,0
  4405.2   0.035       0  5019.2   0.035       0  5023.5   0.035       0
Bank Sta=5019.2,5023.5
Exp/Cntr=0.3,0.1

Type RM Length L Ch R = 1,1822,267,267,267
BEGIN DESCRIPTION:
Mapping XS d2858bea
END DESCRIPTION:
XS GIS Cut Line= 3
      1672252.45      6940768.31      1672044.10      6940983.61
      1671769.00      6941168.74
#Sta/Elev= 30
  4704.0 1826.30  4716.2 1825.81  4730.4 1825.92  4843.3 1824.79  4928.2 1822.87
  4949.5 1823.36  4956.5 1822.73  4963.7 1823.50  4970.6 1822.38  4977.8 1822.59
  4996.8 1819.70  4997.1 1819.20  5000.8 1819.20  5001.1 1819.70  5020.5 1819.70
  5035.5 1822.05  5062.8 1822.87  5077.5 1823.02  5086.5 1822.74  5092.5 1823.24
  5158.5 1823.19  5164.5 1823.81  5171.3 1823.95  5179.5 1823.68  5194.4 1823.90
  5200.5 1823.17  5221.5 1824.03  5272.5 1824.13  5329.5 1823.87  5335.2 1823.59
#Mann=3,-1,0
  4704.0   0.035       0  4996.8   0.035       0  5001.1   0.035       0
Bank Sta=4996.8,5001.1
Exp/Cntr=0.3,0.1

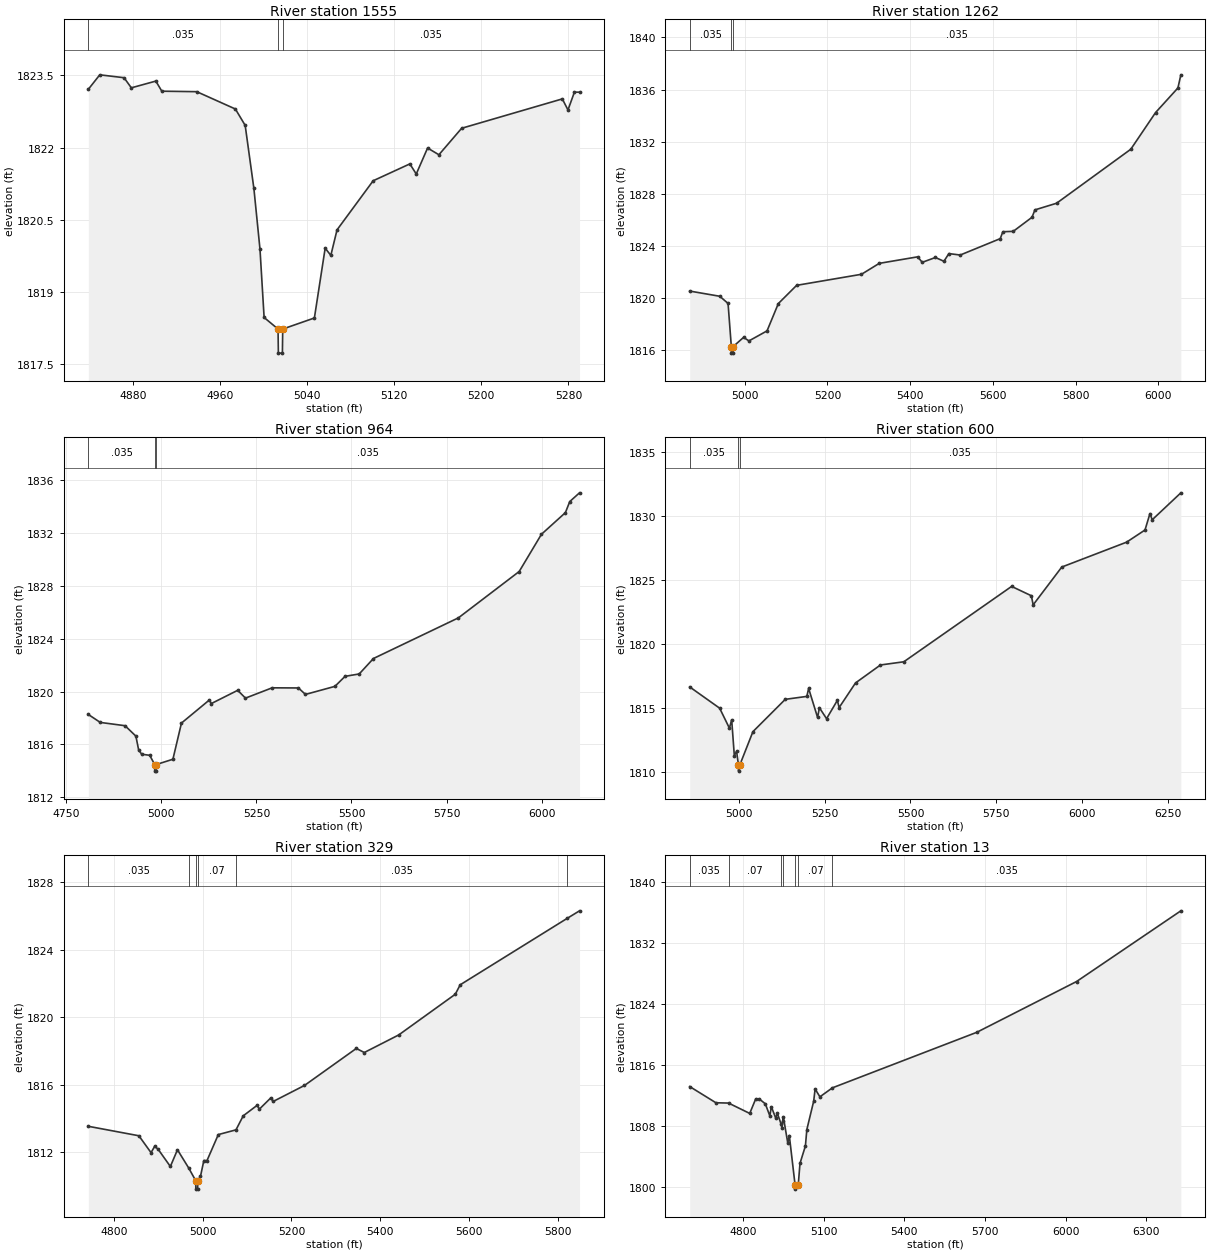
Type RM Length L Ch R = 1,1555,293,293,293
BEGIN DESCRIPTION:
Mapping XS a20cec92
END DESCRIPTION:
XS GIS Cut Line= 3
      1671927.79      6940648.52      1671856.60      6940794.38
      1671776.74      6941072.13
#Sta/Elev= 30
  4838.9 1823.21  4849.4 1823.51  4871.7 1823.45  4878.4 1823.24  4900.9 1823.38
  4906.4 1823.17  4938.5 1823.16  4974.0 1822.80  4983.0 1822.46  4991.0 1821.15
  4996.6 1819.89  5000.4 1818.47  5013.2 1818.23  5013.5 1817.73  5017.2 1817.73
  5017.5 1818.23  5046.6 1818.46  5056.5 1819.91  5061.7 1819.76  5067.4 1820.29
  5100.6 1821.31  5134.3 1821.66  5140.2 1821.45  5150.6 1821.99  5161.0 1821.85
  5181.9 1822.40  5274.4 1823.01  5279.6 1822.78  5285.5 1823.15  5290.2 1823.15
#Mann=3,-1,0
  4838.9   0.035       0  5013.2   0.035       0  5017.5   0.035       0
Bank Sta=5013.2,5017.5
Exp/Cntr=0.3,0.1

Type RM Length L Ch R = 1,1262,298,298,298
BEGIN DESCRIPTION:
Mapping XS 3410596b
END DESCRIPTION:
XS GIS Cut Line= 3
      1671567.97      6940655.28      1671564.98      6940787.95
      1671876.99      6941794.82
#Sta/Elev= 30
  4867.3 1820.51  4940.0 1820.11  4960.0 1819.56  4967.9 1816.24  4968.2 1815.74
  4971.9 1815.74  4972.2 1816.24  4997.5 1816.95  5010.5 1816.68  5054.2 1817.45
  5081.5 1819.55  5125.7 1820.95  5282.4 1821.80  5325.4 1822.64  5418.0 1823.14
  5429.3 1822.72  5461.0 1823.09  5481.6 1822.80  5493.6 1823.39  5521.0 1823.28
  5617.7 1824.54  5624.0 1825.07  5649.1 1825.10  5694.4 1826.18  5701.5 1826.75
  5753.8 1827.26  5933.1 1831.41  5993.0 1834.23  6047.0 1836.12  6054.1 1837.13
#Mann=3,-1,0
  4867.3   0.035       0  4967.9   0.035       0  4972.2   0.035       0
Bank Sta=4967.9,4972.2
Exp/Cntr=0.3,0.1

Type RM Length L Ch R = 1,964,364,364,364
BEGIN DESCRIPTION:
Mapping XS ae8175b8
END DESCRIPTION:
XS GIS Cut Line= 3
      1671387.07      6940676.86      1671280.76      6940841.75
      1671619.24      6941883.24
#Sta/Elev= 30
  4808.2 1818.27  4839.5 1817.67  4904.7 1817.42  4933.2 1816.63  4940.4 1815.59
  4948.4 1815.26  4969.5 1815.18  4982.6 1814.48  4982.8 1813.98  4986.6 1813.98
  4986.9 1814.48  5030.5 1814.88  5053.0 1817.62  5126.4 1819.37  5131.6 1819.10
  5200.8 1820.10  5221.3 1819.51  5291.4 1820.29  5360.5 1820.28  5379.0 1819.79
  5456.4 1820.40  5483.1 1821.16  5520.3 1821.34  5557.7 1822.51  5781.1 1825.59
  5940.9 1829.10  5999.4 1831.92  6062.4 1833.56  6073.9 1834.40  6099.5 1835.06
#Mann=3,-1,0
  4808.2   0.035       0  4982.6   0.035       0  4986.9   0.035       0
Bank Sta=4982.6,4986.9
Exp/Cntr=0.3,0.1

Type RM Length L Ch R = 1,600,271,271,271
BEGIN DESCRIPTION:
Mapping XS 2d682713
END DESCRIPTION:
XS GIS Cut Line= 3
      1671029.03      6940678.98      1670929.20      6940794.01
      1671339.36      6942007.13
#Sta/Elev= 30
  4855.9 1816.67  4943.3 1815.01  4971.8 1813.45  4978.4 1814.11  4986.1 1811.31
  4992.7 1811.65  4998.1 1810.60  4998.4 1810.10  5002.4 1810.60  5040.4 1813.18
  5134.7 1815.70  5197.6 1815.93  5202.9 1816.55  5229.0 1814.29  5234.3 1815.05
  5255.2 1814.19  5286.7 1815.62  5291.9 1815.06  5339.7 1816.98  5412.4 1818.38
  5480.6 1818.63  5795.1 1824.51  5852.7 1823.78  5857.9 1823.07  5941.4 1826.02
  6130.4 1827.96  6184.2 1828.91  6198.6 1830.19  6205.3 1829.71  6288.8 1831.81
#Mann=3,-1,0
  4855.9   0.035       0  4998.1   0.035       0  5002.4   0.035       0
Bank Sta=4998.1,5002.4
Exp/Cntr=0.3,0.1

Type RM Length L Ch R = 1,329,316,316,316
BEGIN DESCRIPTION:
Mapping XS 414917b2
END DESCRIPTION:
XS GIS Cut Line= 3
      1670827.42      6940657.35      1670699.38      6940887.40
      1670981.51      6941681.70
#Sta/Elev= 30
  4742.6 1813.54  4856.4 1812.98  4883.8 1811.98  4892.1 1812.36  4899.8 1812.18
  4927.3 1811.16  4943.3 1812.15  4968.4 1811.08  4984.4 1810.32  4984.7 1809.82
  4988.7 1809.82  4989.0 1810.32  4995.1 1810.57  5002.7 1811.51  5009.8 1811.51
  5035.3 1813.05  5075.1 1813.33  5091.4 1814.16  5122.6 1814.78  5127.9 1814.56
  5153.4 1815.22  5158.8 1815.01  5229.4 1815.96  5346.1 1818.15  5364.1 1817.91
  5441.6 1818.95  5569.0 1821.36  5580.1 1821.92  5821.4 1825.86  5848.8 1826.30
#Mann=6,-1,0
  4742.6   0.035       0  4968.4    0.07       0  4984.4    0.07       0
  4989.0    0.07       0  5075.1   0.035       0  5821.4    0.07       0
Bank Sta=4984.4,4989
Exp/Cntr=0.3,0.1

Type RM Length L Ch R = 1,13,0,0,0
BEGIN DESCRIPTION:
Chimney Creek 1103 1.0
END DESCRIPTION:
XS GIS Cut Line= 3
      1670774.54      6940607.71      1670417.96      6940787.62
      1670898.14      6942133.53
#Sta/Elev= 30
  4600.6 1813.15  4698.2 1811.02  4745.2 1810.98  4824.1 1809.62  4846.5 1811.54
  4859.9 1811.51  4882.2 1810.88  4898.9 1809.30  4904.5 1810.50  4921.2 1808.98
  4926.8 1809.65  4940.8 1808.23  4943.5 1807.77  4946.9 1808.63  4949.1 1809.19
  4965.8 1805.72  4971.4 1806.72  4993.1 1800.18  4993.6 1799.68  5004.6 1800.18
  5011.2 1803.06  5031.4 1805.35  5036.7 1807.50  5062.2 1811.23  5067.5 1812.83
  5085.3 1811.80  5131.9 1812.98  5669.3 1820.27  6040.9 1826.94  6429.0 1836.22
#Mann=7,-1,0
  4600.6   0.035       0  4745.2    0.07       0  4940.8   0.035       0
  4946.9    0.07       0  4993.1    0.07       0  5004.6    0.07       0
  5131.9   0.035       0
Bank Sta=4993.1,5004.6
Exp/Cntr=0.3,0.1

Chan Stop Cuts=-1