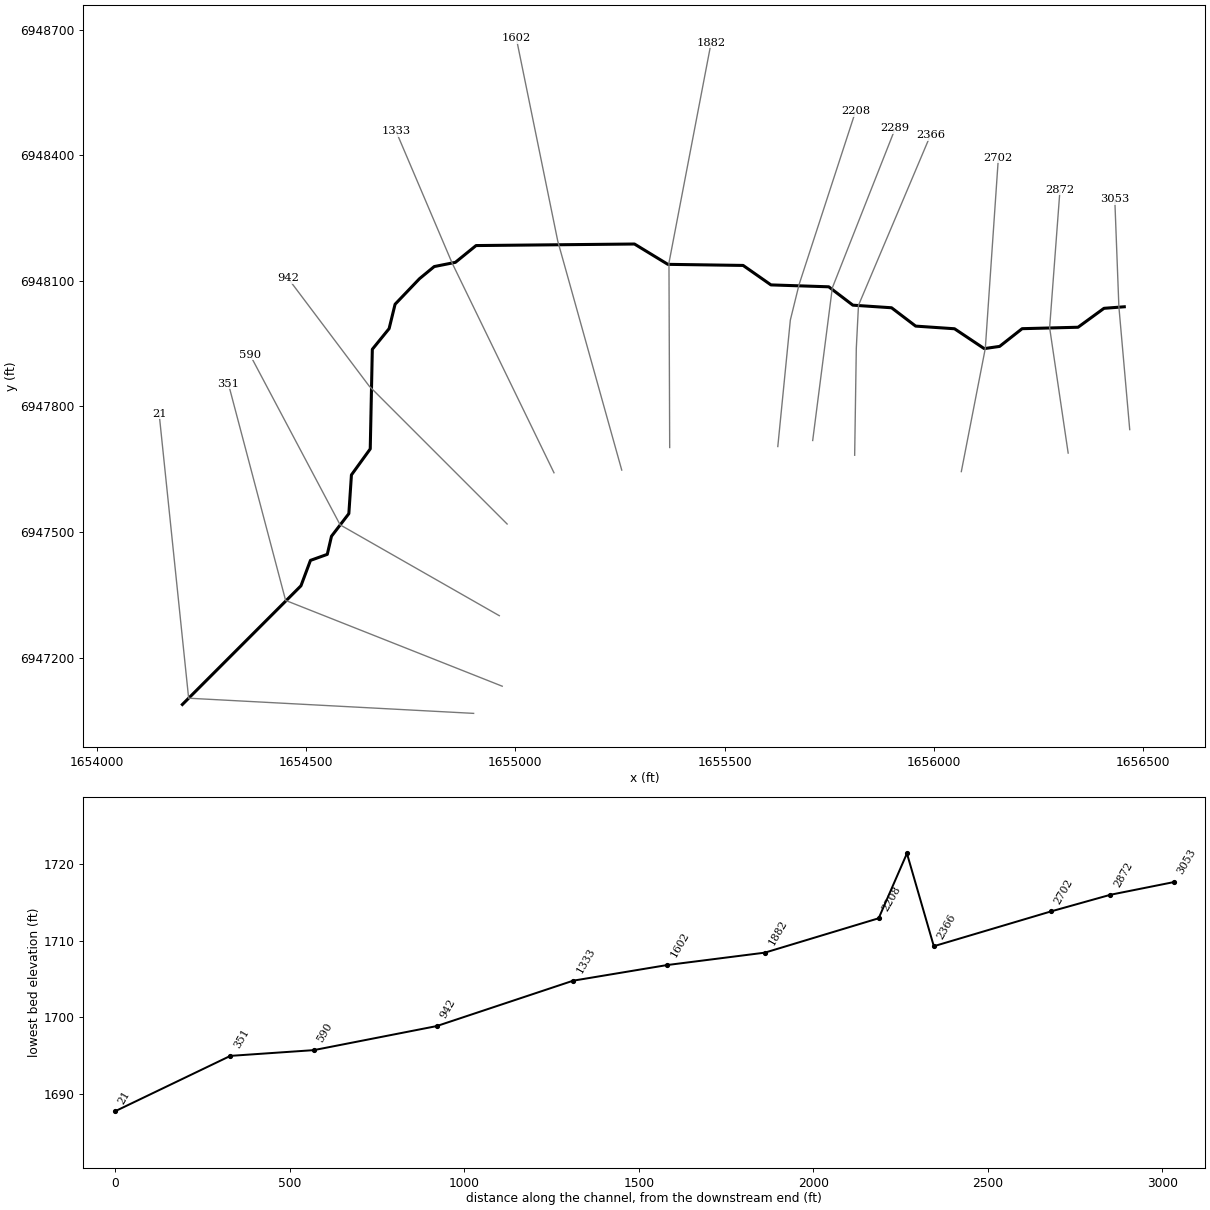
--- Chimney Creek 1104.prj (project) ---

Proj Title=Chimney Creek 1104 Base Level Engineering
Current Plan=p01
Default Exp/Contr=0.3,0.1
English Units
Geom File=g01
Flow File=f01
Plan File=p01
BEGIN DESCRIPTION:
Chimney Creek 1104
END DESCRIPTION:

--- Chimney Creek 1104.p01 (plan) ---

Plan Title=Multiple Run
Short Identifier=Multiple
Geom File=g01
Flow File=f01
Subcritical Flow
K Sum by GR= 0
Std Step Tol= 0.01
Critical Tol= 0.01
Num of Std Step Trials= 20
Max Error Tol= 0.3
Flow Tol Ratio= 0.001
Split Flow NTrial= 30
Split Flow Tol= 0.02
Split Flow Ratio= 0.02
Log Output Level= 0
Friction Slope Method= 1
Unsteady Friction Slope Method= 2
Unsteady Bridges Friction Slope Method= 1
Parabolic Critical Depth
Global Vel Dist=  1 , 1 , 1
Global Log Level= 0
CheckData=True
Encroach Param= -1, 0, 0, 0
BEGIN DESCRIPTION:
Multiple Run
END DESCRIPTION:

--- Chimney Creek 1104.f01 (steady flow) ---

Flow Title=Multiple
Number of Profiles=7
Profile Names=10-year,25-year,50-year,1pct_min,100-year,1pct_plu,500-year
River Rch & RM= Chimney Creek 11,Reach-1,3053
     269     376     465     287     573    1144     881
River Rch & RM= Chimney Creek 11,Reach-1,2702
     292     410     508     314     627    1251     966
River Rch & RM= Chimney Creek 11,Reach-1,21
    1807    2691    3472    2218    4426    8830    7285
Boundary for River Rch & Prof#=Chimney Creek 11,Reach-1,1
Up Type=0
Dn Type=3
Dn Slope=0.005
Boundary for River Rch & Prof#=Chimney Creek 11,Reach-1,2
Up Type=0
Dn Type=3
Dn Slope=0.005
Boundary for River Rch & Prof#=Chimney Creek 11,Reach-1,3
Up Type=0
Dn Type=3
Dn Slope=0.005
Boundary for River Rch & Prof#=Chimney Creek 11,Reach-1,4
Up Type=0
Dn Type=3
Dn Slope=0.005
Boundary for River Rch & Prof#=Chimney Creek 11,Reach-1,5
Up Type=0
Dn Type=3
Dn Slope=0.005
Boundary for River Rch & Prof#=Chimney Creek 11,Reach-1,6
Up Type=0
Dn Type=3
Dn Slope=0.005
Boundary for River Rch & Prof#=Chimney Creek 11,Reach-1,7
Up Type=0
Dn Type=3
Dn Slope=0.005

--- Chimney Creek 1104.g01 (geometry) ---

Geom Title=Existing Conditions

River Reach=Chimney Creek 11,Reach-1
Reach XY= 30
      1656455.00      6948038.00      1656406.51      6948034.35
      1656344.53      6947989.13      1656210.93      6947985.70
      1656157.18      6947943.38      1656120.39      6947938.09
      1656049.44      6947985.51      1655956.60      6947991.85
      1655899.03      6948035.65      1655806.60      6948041.86
      1655749.06      6948085.73      1655610.94      6948090.27
      1655544.49      6948136.78      1655364.66      6948139.38
      1655284.97      6948187.93      1654906.55      6948184.25
      1654857.17      6948144.14      1654806.62      6948134.06
      1654771.42      6948105.08      1654713.13      6948044.07
      1654698.86      6947985.83      1654658.75      6947936.45
      1654653.78      6947698.50      1654608.86      6947636.40
      1654602.68      6947543.94      1654561.22      6947489.86
      1654551.16      6947446.62      1654510.99      6947432.23
      1654488.29      6947371.51      1654205.00      6947088.00

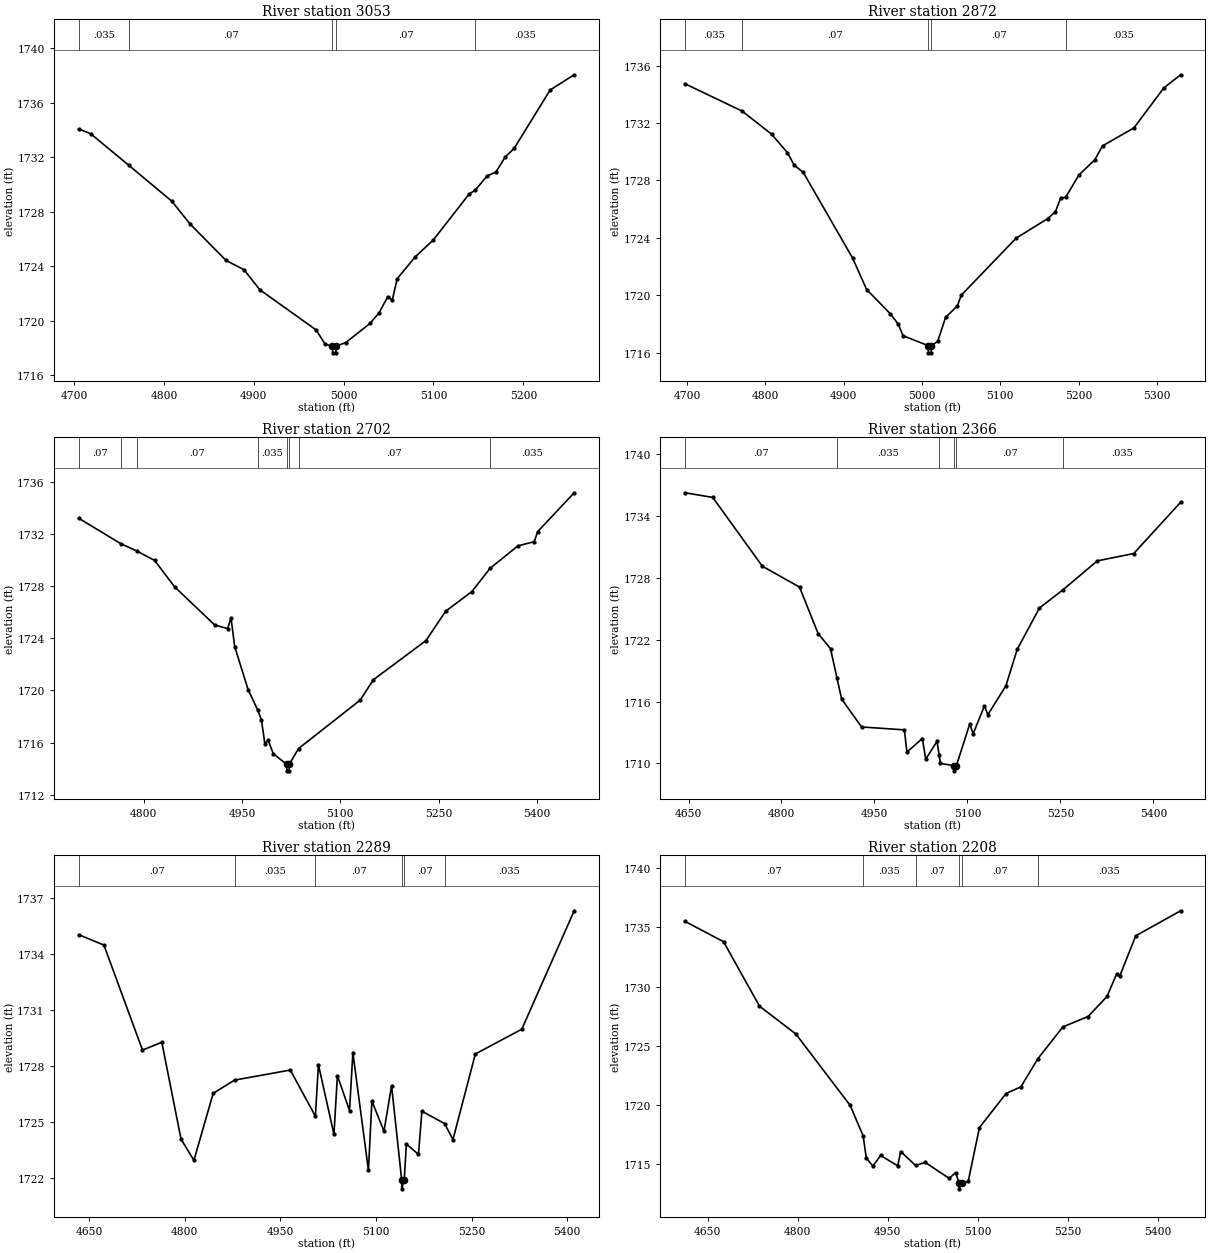
Type RM Length L Ch R = 1,3053,181,181,181
BEGIN DESCRIPTION:
Chimney Creek 1104 6.0
END DESCRIPTION:
XS GIS Cut Line= 3
      1656467.95      6947744.62      1656442.04      6948038.38
      1656432.26      6948294.79
#Sta/Elev= 30
  4705.1 1734.09  4718.5 1733.74  4760.8 1731.43  4808.9 1728.78  4829.0 1727.12
  4869.1 1724.44  4889.2 1723.75  4906.8 1722.28  4969.5 1719.33  4979.5 1718.27
  4987.6 1718.15  4987.8 1717.65  4991.3 1717.65  4991.6 1718.15  5002.3 1718.40
  5029.6 1719.82  5039.7 1720.61  5049.1 1721.77  5054.1 1721.52  5059.7 1723.10
  5079.7 1724.70  5099.7 1725.93  5139.7 1729.31  5146.5 1729.60  5159.7 1730.64
  5169.7 1730.94  5179.8 1732.03  5189.8 1732.66  5229.8 1736.95  5256.6 1738.07
#Mann=5,-1,0
  4705.1   0.035       0  4760.8    0.07       0  4987.6    0.07       0
  4991.6    0.07       0  5146.5   0.035       0
Bank Sta=4987.6,4991.6
Exp/Cntr=0.3,0.1

Type RM Length L Ch R = 1,2872,170,170,170
BEGIN DESCRIPTION:
Mapping XS 2be79e79
END DESCRIPTION:
XS GIS Cut Line= 3
      1656320.90      6947688.59      1656276.63      6947988.08
      1656301.37      6948317.50
#Sta/Elev= 30
  4697.3 1734.73  4770.2 1732.83  4807.9 1731.22  4828.1 1729.93  4836.7 1729.07
  4848.3 1728.56  4911.3 1722.60  4929.2 1720.41  4959.5 1718.72  4969.6 1718.00
  4975.8 1717.19  5008.0 1716.50  5008.2 1716.00  5011.7 1716.00  5012.0 1716.50
  5020.0 1716.80  5030.1 1718.47  5045.1 1719.26  5050.1 1720.01  5120.3 1723.99
  5160.4 1725.34  5170.4 1725.82  5177.0 1726.76  5183.5 1726.83  5200.5 1728.39
  5220.6 1729.43  5230.6 1730.41  5270.7 1731.66  5309.0 1734.45  5330.4 1735.36
#Mann=5,-1,0
  4697.3   0.035       0  4770.2    0.07       0  5008.0    0.07       0
  5012.0    0.07       0  5183.5   0.035       0
Bank Sta=5008,5012
Exp/Cntr=0.3,0.1

Type RM Length L Ch R = 1,2702,336,336,336
BEGIN DESCRIPTION:
Mapping XS 44bd71e6
END DESCRIPTION:
XS GIS Cut Line= 3
      1656065.69      6947644.31      1656122.98      6947938.60
      1656154.18      6948393.62
#Sta/Elev= 30
  4700.9 1733.19  4765.2 1731.24  4789.2 1730.69  4816.7 1729.96  4847.3 1727.93
  4908.4 1725.01  4928.2 1724.73  4933.3 1725.57  4939.0 1723.34  4959.4 1720.06
  4973.8 1718.52  4979.7 1717.75  4985.0 1715.90  4990.1 1716.16  4997.9 1715.14
  5018.2 1714.33  5018.4 1713.83  5021.9 1713.83  5022.2 1714.33  5036.4 1715.54
  5130.4 1719.25  5150.5 1720.81  5230.7 1723.81  5260.7 1726.06  5300.8 1727.57
  5328.5 1729.35  5371.0 1731.07  5395.8 1731.39  5401.1 1732.16  5456.8 1735.14
#Mann=8,-1,0
  4700.9    0.07       0  4765.2   0.035       0  4789.2    0.07       0
  4973.8   0.035       0  5018.2   0.035       0  5022.2   0.035       0
  5036.4    0.07       0  5328.5   0.035       0
Bank Sta=5018.2,5022.2
Exp/Cntr=0.3,0.1

Type RM Length L Ch R = 1,2366,77,77,77
BEGIN DESCRIPTION:
Mapping XS dad306c0
END DESCRIPTION:
XS GIS Cut Line= 4
      1655810.92      6947683.38      1655814.82      6947938.60
      1655820.03      6948041.47      1655991.92      6948447.75
#Sta/Elev= 30
  4644.5 1736.28  4689.1 1735.83  4769.1 1729.15  4829.1 1727.12  4859.1 1722.61
  4879.1 1721.14  4889.6 1718.26  4897.0 1716.25  4929.2 1713.54  4998.2 1713.26
  5002.4 1711.10  5027.2 1712.42  5032.7 1710.41  5050.9 1712.15  5054.3 1710.83
  5056.4 1710.01  5078.0 1709.78  5078.2 1709.28  5082.1 1709.78  5103.7 1713.83
  5109.2 1712.88  5127.4 1715.59  5132.9 1714.73  5162.0 1717.53  5180.2 1721.07
  5216.1 1725.09  5253.9 1726.85  5309.5 1729.67  5368.2 1730.38  5443.9 1735.36
#Mann=6,-1,0
  4644.5    0.07       0  4889.6   0.035       0  5054.3    0.07       0
  5078.0   0.035       0  5082.1    0.07       0  5253.9   0.035       0
Bank Sta=5078,5082.1
Exp/Cntr=0.3,0.1

Type RM Length L Ch R = 1,2289,81,81,81
BEGIN DESCRIPTION:
Mapping XS 7f4271ed
END DESCRIPTION:
XS GIS Cut Line= 3
      1655710.66      6947718.59      1655757.53      6948083.14
      1655907.99      6948464.48
#Sta/Elev= 30
  4633.4 1735.03  4673.1 1734.47  4733.6 1728.84  4763.9 1729.26  4794.1 1724.06
  4814.3 1722.93  4844.5 1726.52  4878.0 1727.23  4965.5 1727.77  5004.9 1725.29
  5009.6 1728.06  5034.0 1724.32  5039.4 1727.47  5058.4 1725.60  5063.7 1728.70
  5088.1 1722.39  5093.5 1726.11  5112.5 1724.49  5124.4 1726.93  5140.2 1721.90
  5140.4 1721.40  5144.3 1721.90  5147.6 1723.80  5166.6 1723.25  5172.0 1725.56
  5207.7 1724.90  5220.7 1724.04  5255.8 1728.63  5328.7 1729.96  5410.9 1736.31
#Mann=6,-1,0
  4633.4    0.07       0  4878.0   0.035       0  5004.9    0.07       0
  5140.2   0.035       0  5144.3    0.07       0  5207.7   0.035       0
Bank Sta=5140.2,5144.3
Exp/Cntr=0.3,0.1

Type RM Length L Ch R = 1,2208,326,326,326
BEGIN DESCRIPTION:
Mapping XS c4ba174d
END DESCRIPTION:
XS GIS Cut Line= 4
      1655627.32      6947704.19      1655657.27      6948006.31
      1655678.10      6948090.95      1655812.98      6948504.66
#Sta/Elev= 30
  4612.3 1735.49  4676.4 1733.78  4736.3 1728.34  4797.0 1725.99  4887.4 1719.97
  4909.1 1717.40  4914.2 1715.55  4925.1 1714.84  4938.2 1715.75  4966.6 1714.87
  4971.7 1716.08  4996.5 1714.90  5012.5 1715.16  5052.5 1713.81  5063.1 1714.30
  5069.0 1713.43  5069.2 1712.93  5073.1 1713.43  5084.1 1713.55  5102.9 1718.10
  5147.2 1720.97  5172.0 1721.54  5200.3 1723.91  5241.9 1726.59  5283.9 1727.47
  5315.5 1729.16  5331.5 1731.06  5336.8 1730.89  5363.4 1734.28  5438.2 1736.39
#Mann=6,-1,0
  4612.3    0.07       0  4909.1   0.035       0  4996.5    0.07       0
  5069.0    0.07       0  5073.1    0.07       0  5200.3   0.035       0
Bank Sta=5069,5073.1
Exp/Cntr=0.3,0.1

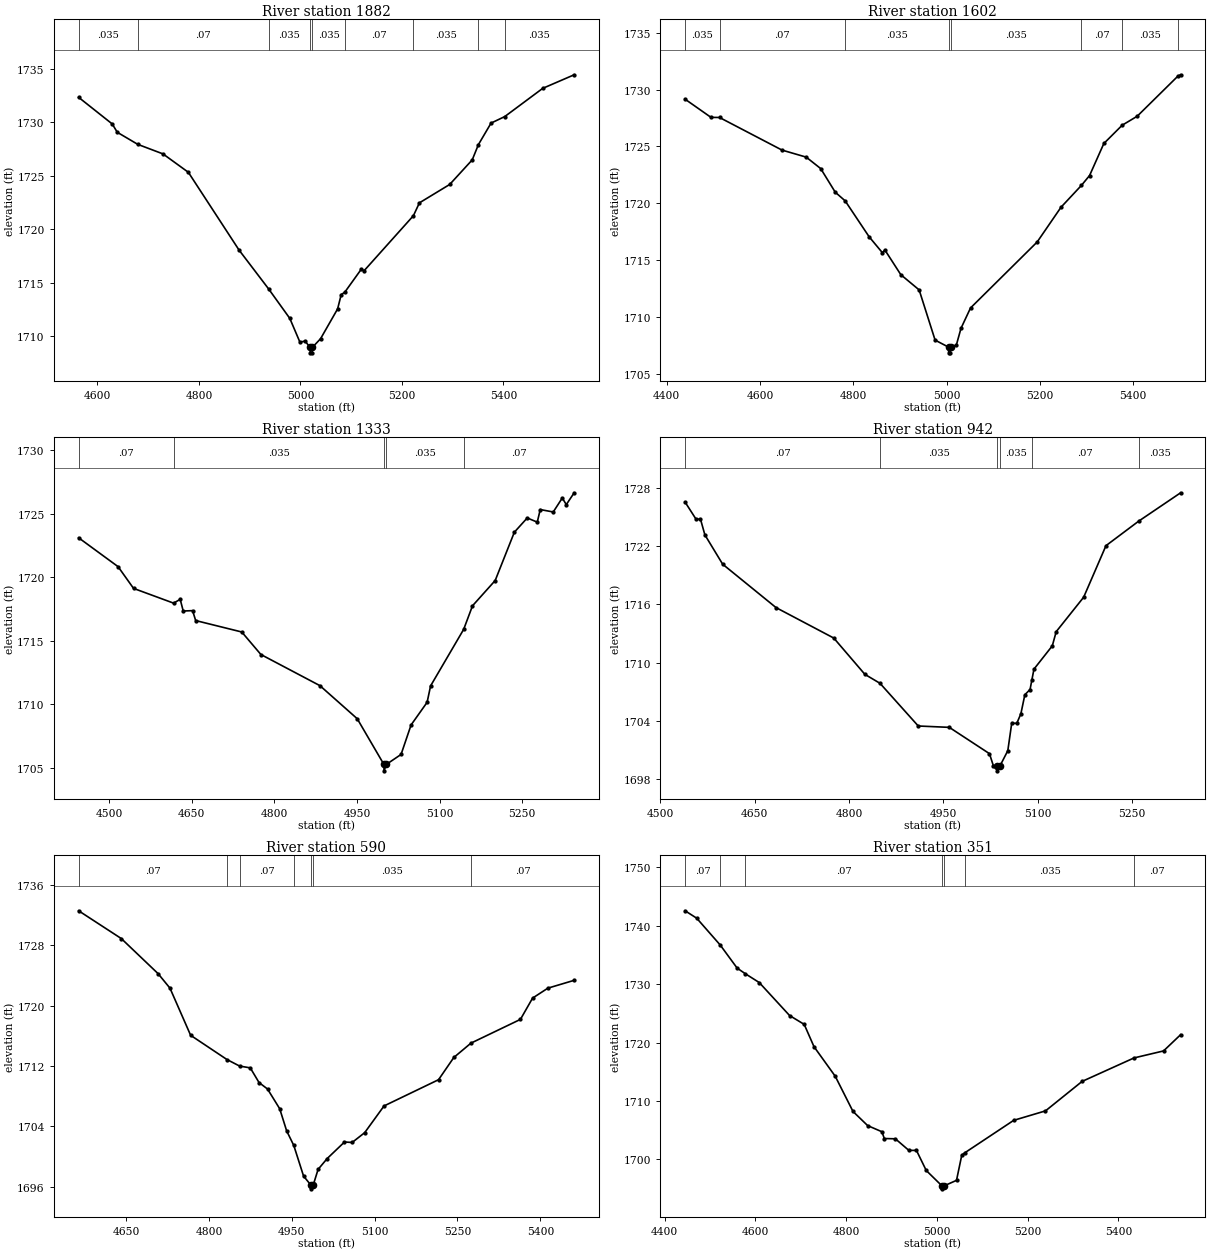
Type RM Length L Ch R = 1,1882,280,280,280
BEGIN DESCRIPTION:
Mapping XS 093577ab
END DESCRIPTION:
XS GIS Cut Line= 3
      1655369.08      6947701.84      1655367.34      6948142.82
      1655468.04      6948668.89
#Sta/Elev= 30
  4562.9 1732.34  4629.1 1729.85  4639.1 1729.07  4679.5 1727.94  4729.1 1727.05
  4779.1 1725.33  4879.1 1718.05  4937.3 1714.42  4979.1 1711.66  4999.0 1709.44
  5009.2 1709.54  5019.2 1708.94  5019.4 1708.44  5023.0 1708.44  5023.3 1708.94
  5039.7 1709.76  5073.3 1712.55  5080.4 1713.89  5087.4 1714.11  5120.2 1716.28
  5125.3 1716.11  5222.7 1721.27  5234.5 1722.47  5294.2 1724.19  5338.6 1726.49
  5350.8 1727.92  5375.7 1729.93  5402.7 1730.54  5477.5 1733.18  5539.5 1734.45
#Mann=9,-1,0
  4562.9   0.035       0  4679.5    0.07       0  4937.3   0.035       0
  5019.2   0.035       0  5023.3   0.035       0  5087.4    0.07       0
  5222.7   0.035       0  5350.8    0.07       0  5402.7   0.035       0
Bank Sta=5019.2,5023.3
Exp/Cntr=0.3,0.1

Type RM Length L Ch R = 1,1602,269,269,269
BEGIN DESCRIPTION:
Mapping XS bcb8c768
END DESCRIPTION:
XS GIS Cut Line= 3
      1655254.50      6947647.99      1655101.71      6948194.90
      1655002.76      6948679.24
#Sta/Elev= 30
  4439.3 1729.15  4494.8 1727.55  4513.1 1727.54  4647.0 1724.67  4698.9 1724.05
  4730.0 1723.04  4761.2 1720.96  4782.4 1720.20  4833.9 1717.03  4862.3 1715.63
  4867.5 1715.88  4901.7 1713.70  4941.0 1712.36  4975.2 1707.94  5004.1 1707.32
  5004.3 1706.82  5008.0 1706.82  5008.3 1707.32  5020.7 1707.50  5030.7 1708.98
  5051.1 1710.77  5194.0 1716.58  5245.1 1719.64  5288.8 1721.56  5306.3 1722.43
  5336.9 1725.25  5376.2 1726.86  5408.4 1727.65  5495.6 1731.18  5501.5 1731.30
#Mann=8,-1,0
  4439.3   0.035       0  4513.1    0.07       0  4782.4   0.035       0
  5004.1   0.035       0  5008.3   0.035       0  5288.8    0.07       0
  5376.2   0.035       0  5495.6    0.07       0
Bank Sta=5004.1,5008.3
Exp/Cntr=0.3,0.1

Type RM Length L Ch R = 1,1333,391,391,391
BEGIN DESCRIPTION:
Mapping XS 532d3d6d
END DESCRIPTION:
XS GIS Cut Line= 3
      1655092.69      6947641.55      1654849.22      6948142.82
      1654715.11      6948457.90
#Sta/Elev= 30
  4444.6 1723.11  4516.2 1720.84  4544.3 1719.13  4617.0 1717.97  4629.0 1718.27
  4634.5 1717.35  4651.5 1717.38  4657.1 1716.60  4740.8 1715.70  4775.5 1713.93
  4882.7 1711.48  4950.4 1708.88  4998.9 1705.28  4999.1 1704.78  5003.1 1705.28
  5030.0 1706.07  5048.2 1708.39  5077.3 1710.17  5083.6 1711.46  5143.7 1715.91
  5159.7 1717.76  5200.9 1719.75  5235.7 1723.55  5259.1 1724.67  5277.3 1724.34
  5282.7 1725.33  5306.3 1725.14  5322.7 1726.24  5330.0 1725.72  5344.3 1726.65
#Mann=5,-1,0
  4444.6    0.07       0  4617.0   0.035       0  4998.9   0.035       0
  5003.1   0.035       0  5143.7    0.07       0
Bank Sta=4998.9,5003.1
Exp/Cntr=0.3,0.1

Type RM Length L Ch R = 1,942,352,352,352
BEGIN DESCRIPTION:
Mapping XS 5b3dd910
END DESCRIPTION:
XS GIS Cut Line= 3
      1654980.73      6947519.12      1654651.30      6947848.54
      1654457.31      6948106.33
#Sta/Elev= 30
  4539.2 1726.54  4556.6 1724.78  4563.7 1724.78  4570.7 1723.16  4599.0 1720.14
  4683.9 1715.67  4775.8 1712.53  4825.3 1708.79  4849.3 1707.87  4910.2 1703.47
  4959.6 1703.33  5023.5 1700.62  5029.8 1699.36  5036.0 1699.35  5036.2 1698.85
  5040.2 1699.35  5052.7 1700.93  5058.9 1703.75  5067.0 1703.75  5073.5 1704.73
  5079.8 1706.69  5088.1 1707.23  5091.1 1708.25  5094.3 1709.33  5123.5 1711.73
  5129.7 1713.19  5173.4 1716.74  5208.9 1722.05  5260.8 1724.57  5327.7 1727.50
#Mann=6,-1,0
  4539.2    0.07       0  4849.3   0.035       0  5036.0   0.035       0
  5040.2   0.035       0  5091.1    0.07       0  5260.8   0.035       0
Bank Sta=5036,5040.2
Exp/Cntr=0.3,0.1

Type RM Length L Ch R = 1,590,239,239,239
BEGIN DESCRIPTION:
Mapping XS 4ec099e2
END DESCRIPTION:
XS GIS Cut Line= 3
      1654962.05      6947300.12      1654581.86      6947517.12
      1654366.69      6947923.17
#Sta/Elev= 30
  4564.0 1732.58  4641.2 1728.90  4707.8 1724.25  4729.4 1722.32  4766.8 1716.07
  4832.7 1712.85  4855.5 1711.99  4874.8 1711.75  4890.7 1709.80  4906.0 1708.95
  4928.1 1706.33  4940.6 1703.41  4953.6 1701.46  4971.3 1697.40  4984.5 1696.21
  4984.8 1695.71  4988.8 1696.21  4997.6 1698.29  5014.1 1699.73  5045.4 1701.92
  5059.3 1701.86  5082.0 1703.16  5117.0 1706.70  5215.7 1710.18  5243.4 1713.13
  5274.4 1715.03  5364.0 1718.18  5386.0 1721.00  5413.7 1722.32  5461.3 1723.36
#Mann=7,-1,0
  4564.0    0.07       0  4832.7   0.035       0  4855.5    0.07       0
  4953.6   0.035       0  4984.5   0.035       0  4988.8   0.035       0
  5274.4    0.07       0
Bank Sta=4984.5,4988.8
Exp/Cntr=0.3,0.1

Type RM Length L Ch R = 1,351,330,330,330
BEGIN DESCRIPTION:
Mapping XS 3cf8eb82
END DESCRIPTION:
XS GIS Cut Line= 3
      1654969.03      6947131.69      1654451.65      6947336.57
      1654314.85      6947854.33
#Sta/Elev= 30
  4445.2 1742.54  4470.8 1741.27  4522.6 1736.68  4559.9 1732.73  4577.9 1731.77
  4608.6 1730.26  4675.4 1724.62  4707.7 1723.10  4729.2 1719.29  4776.1 1714.22
  4815.2 1708.20  4847.5 1705.78  4878.9 1704.73  4884.2 1703.57  4908.6 1703.52
  4938.3 1701.54  4955.0 1701.54  4976.6 1698.10  5011.3 1695.46  5011.6 1694.96
  5015.6 1695.46  5043.3 1696.41  5054.9 1700.73  5062.0 1701.15  5169.3 1706.68
  5239.4 1708.30  5320.0 1713.34  5434.5 1717.36  5499.6 1718.56  5537.2 1721.34
#Mann=7,-1,0
  4445.2    0.07       0  4522.6   0.035       0  4577.9    0.07       0
  5011.3    0.07       0  5015.6    0.07       0  5062.0   0.035       0
  5434.5    0.07       0
Bank Sta=5011.3,5015.6
Exp/Cntr=0.3,0.1

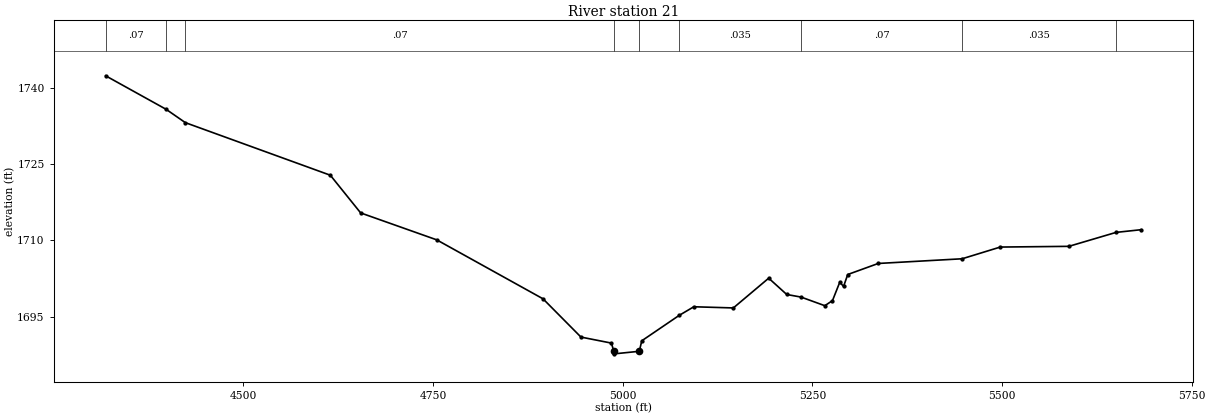
Type RM Length L Ch R = 1,21,0,0,0
BEGIN DESCRIPTION:
Chimney Creek 1104 1.0
END DESCRIPTION:
XS GIS Cut Line= 3
      1654900.74      6947066.78      1654220.00      6947103.00
      1654149.45      6947782.95
#Sta/Elev= 30
  4318.3 1742.31  4398.0 1735.73  4423.4 1733.11  4614.5 1722.79  4654.5 1715.39
  4754.7 1710.11  4894.9 1698.53  4944.9 1691.02  4985.0 1689.84  4988.3 1688.23
  4988.9 1687.73  5021.8 1688.23  5025.1 1690.29  5074.3 1695.27  5093.7 1696.97
  5145.8 1696.74  5192.4 1702.58  5216.2 1699.38  5235.1 1698.87  5266.4 1697.18
  5276.5 1698.18  5286.1 1701.79  5291.1 1700.96  5296.6 1703.30  5336.8 1705.47
  5447.4 1706.39  5497.7 1708.69  5588.1 1708.83  5650.4 1711.57  5683.6 1712.10
#Mann=9,-1,0
  4318.3    0.07       0  4398.0   0.035       0  4423.4    0.07       0
  4988.3    0.07       0  5021.8    0.07       0  5074.3   0.035       0
  5235.1    0.07       0  5447.4   0.035       0  5650.4    0.07       0
Bank Sta=4988.3,5021.8
Exp/Cntr=0.3,0.1

Chan Stop Cuts=-1