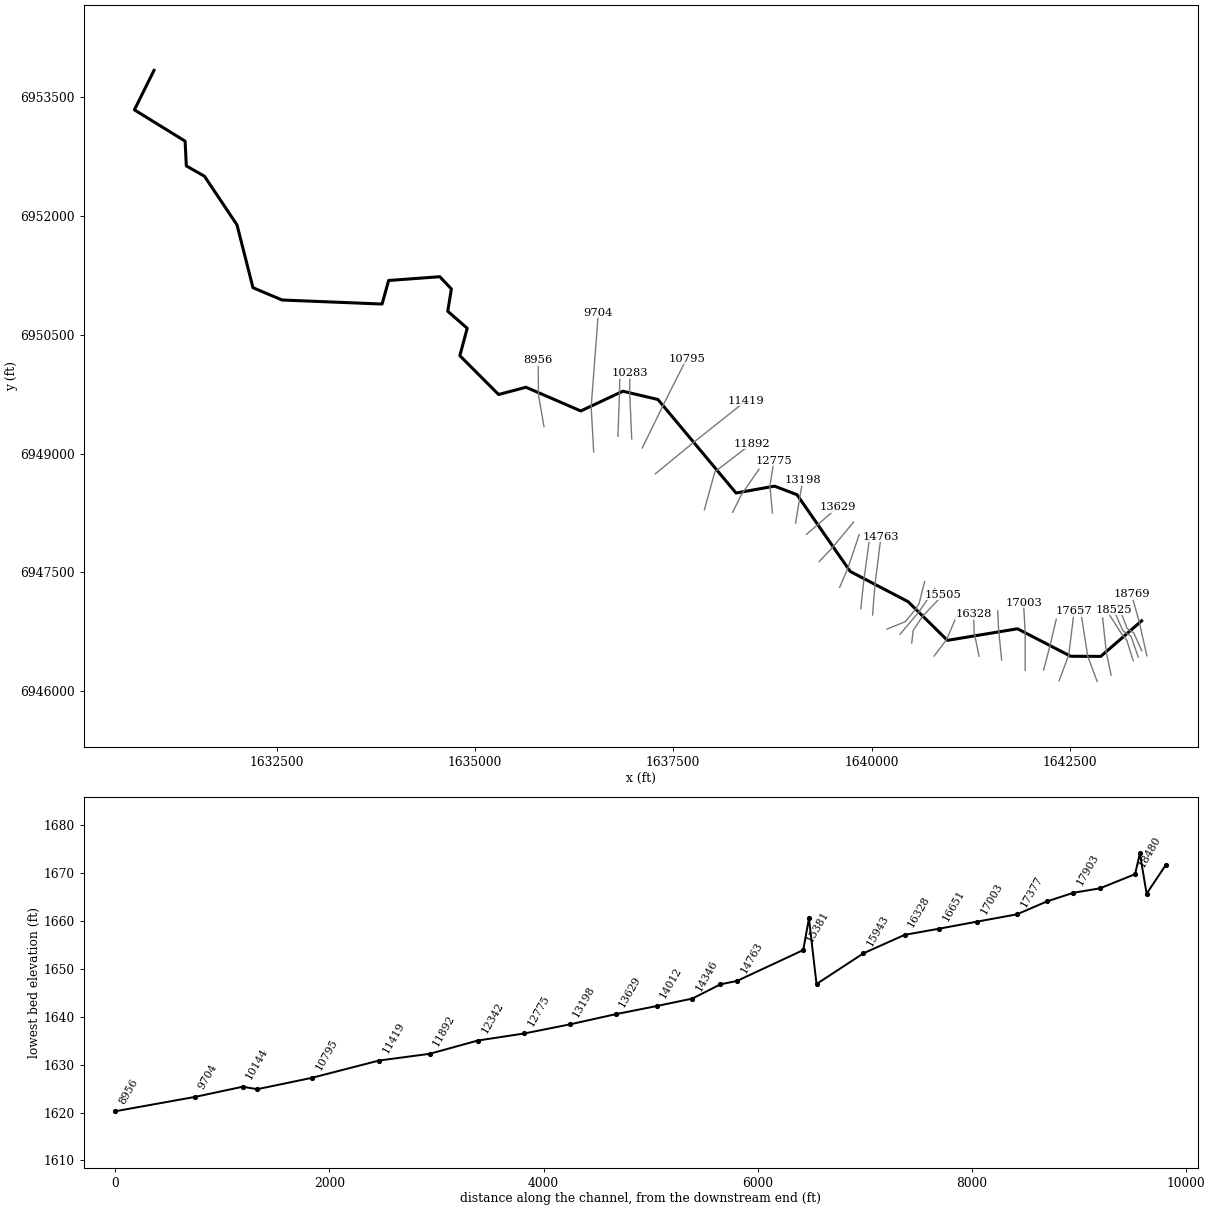
--- Chimney Creek 1105.prj (project) ---

Proj Title=Chimney Creek 1105 Base Level Engineering
Current Plan=p01
Default Exp/Contr=0.3,0.1
English Units
Geom File=g01
Flow File=f01
Plan File=p01
BEGIN DESCRIPTION:
Chimney Creek 1105
END DESCRIPTION:

--- Chimney Creek 1105.p01 (plan) ---

Plan Title=Multiple Run
Short Identifier=Multiple
Geom File=g01
Flow File=f01
Subcritical Flow
K Sum by GR= 0
Std Step Tol= 0.01
Critical Tol= 0.01
Num of Std Step Trials= 20
Max Error Tol= 0.3
Flow Tol Ratio= 0.001
Split Flow NTrial= 30
Split Flow Tol= 0.02
Split Flow Ratio= 0.02
Log Output Level= 0
Friction Slope Method= 1
Unsteady Friction Slope Method= 2
Unsteady Bridges Friction Slope Method= 1
Parabolic Critical Depth
Global Vel Dist=  1 , 1 , 1
Global Log Level= 0
CheckData=True
Encroach Param= -1, 0, 0, 0
BEGIN DESCRIPTION:
Multiple Run
END DESCRIPTION:

--- Chimney Creek 1105.f01 (steady flow) ---

Flow Title=Multiple
Number of Profiles=7
Profile Names=10-year,25-year,50-year,1pct_min,100-year,1pct_plu,500-year
River Rch & RM= Chimney Creek 11,Reach-1,18769
     237     327     401     245     489     976     737
River Rch & RM= Chimney Creek 11,Reach-1,17657
     274     382     471     289     577    1151     878
River Rch & RM= Chimney Creek 11,Reach-1,15943
     320     448     555     342     683    1363    1047
River Rch & RM= Chimney Creek 11,Reach-1,12342
     443     628     784     487     971    1937    1509
River Rch & RM= Chimney Creek 11,Reach-1,3850
     529     756     949     592    1181    2357    1854
River Rch & RM= Chimney Creek 11,Reach-1,1394
     600     863    1088     681    1358    2710    2146
Boundary for River Rch & Prof#=Chimney Creek 11,Reach-1,1
Up Type=0
Dn Type=3
Dn Slope=0.005
Boundary for River Rch & Prof#=Chimney Creek 11,Reach-1,2
Up Type=0
Dn Type=3
Dn Slope=0.005
Boundary for River Rch & Prof#=Chimney Creek 11,Reach-1,3
Up Type=0
Dn Type=3
Dn Slope=0.005
Boundary for River Rch & Prof#=Chimney Creek 11,Reach-1,4
Up Type=0
Dn Type=3
Dn Slope=0.005
Boundary for River Rch & Prof#=Chimney Creek 11,Reach-1,5
Up Type=0
Dn Type=3
Dn Slope=0.005
Boundary for River Rch & Prof#=Chimney Creek 11,Reach-1,6
Up Type=0
Dn Type=3
Dn Slope=0.005
Boundary for River Rch & Prof#=Chimney Creek 11,Reach-1,7
Up Type=0
Dn Type=3
Dn Slope=0.005

--- Chimney Creek 1105.g01 (geometry) ---

Geom Title=Existing Conditions

River Reach=Chimney Creek 11,Reach-1
Reach XY= 30
      1643405.00      6946888.00      1642889.79      6946438.51
      1642510.93      6946440.24      1641839.78      6946787.48
      1640956.63      6946641.13      1640461.06      6947129.86
      1639731.53      6947511.01      1639061.05      6948479.84
      1638777.84      6948588.29      1638291.79      6948501.61
      1637307.45      6949682.54      1636865.45      6949786.96
      1636334.95      6949537.40      1635644.56      6949836.94
      1635298.97      6949745.45      1634810.40      6950235.57
      1634903.38      6950581.97      1634658.14      6950796.05
      1634703.81      6951078.41      1634557.44      6951232.53
      1633912.61      6951184.93      1633830.13      6950887.46
      1632570.21      6950938.51      1632202.69      6951093.82
      1632001.45      6951886.53      1631591.38      6952501.24
      1631362.67      6952631.48      1631347.20      6952944.21
      1630708.12      6953339.63      1630955.00      6953838.00

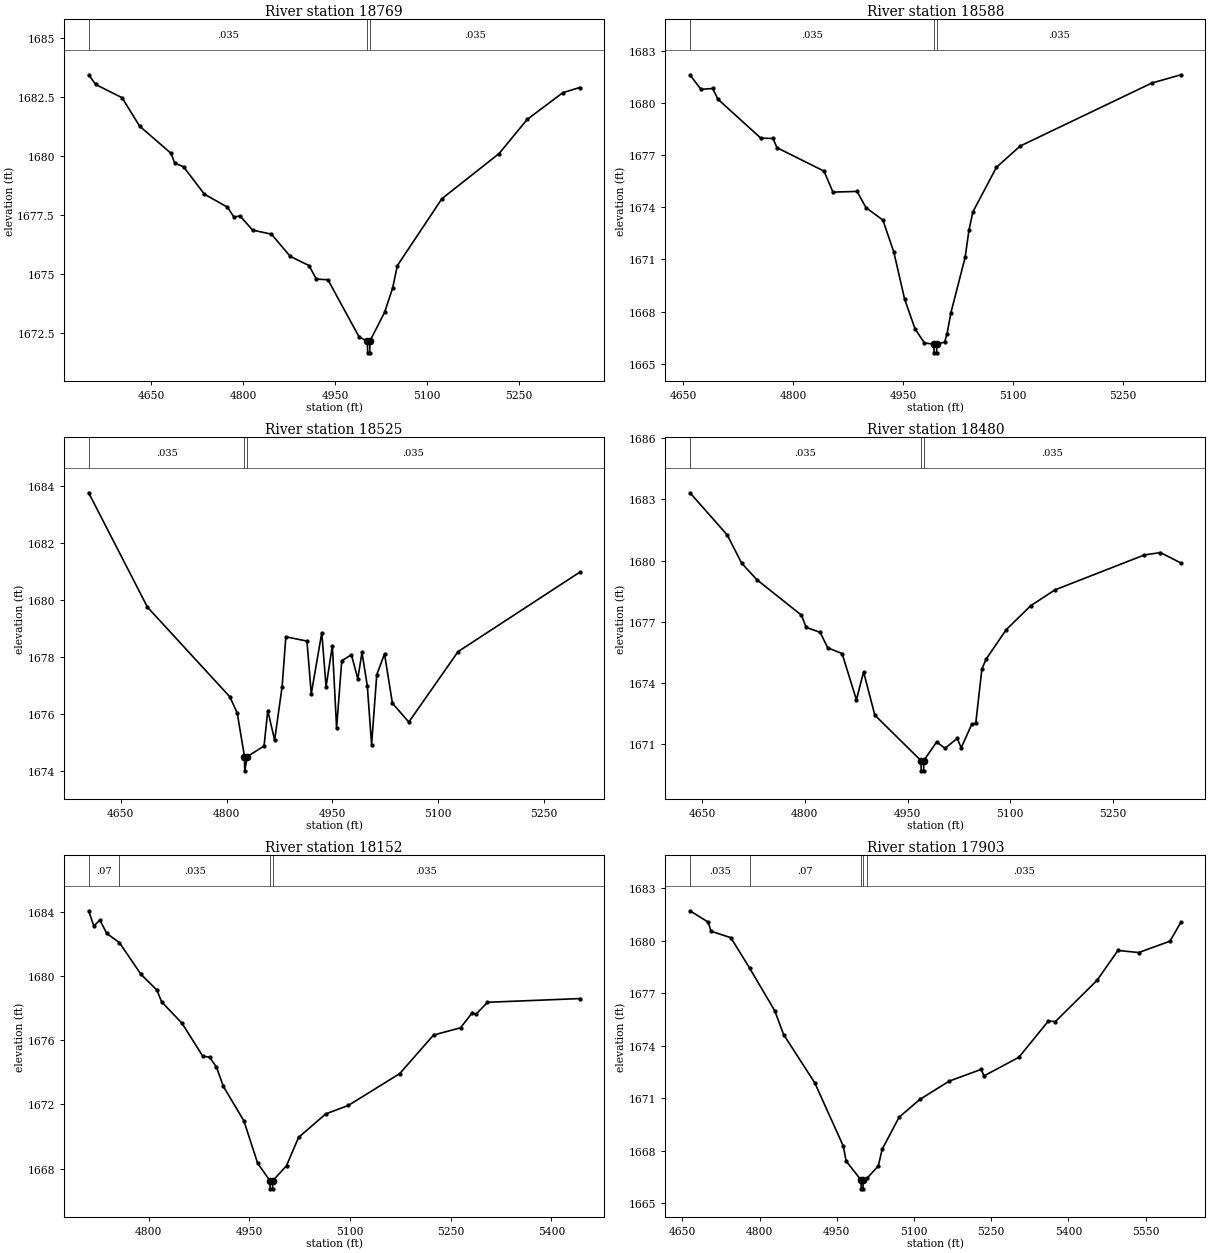
Type RM Length L Ch R = 1,18769,181,181,181
BEGIN DESCRIPTION:
Chimney Creek 1105 28.0
END DESCRIPTION:
XS GIS Cut Line= 3
      1643471.40      6946446.82      1643371.37      6946887.92
      1643276.51      6947224.41
#Sta/Elev= 30
  4547.7 1683.43  4559.2 1683.02  4602.3 1682.46  4630.9 1681.26  4682.2 1680.11
  4688.5 1679.69  4702.7 1679.54  4736.8 1678.38  4774.5 1677.83  4785.0 1677.41
  4795.0 1677.46  4815.5 1676.86  4846.3 1676.69  4877.0 1675.75  4907.8 1675.36
  4919.5 1674.79  4938.6 1674.76  4989.8 1672.33  5003.2 1672.17  5003.4 1671.67
  5006.9 1671.67  5007.2 1672.17  5031.3 1673.39  5044.4 1674.42  5052.0 1675.36
  5124.8 1678.19  5218.3 1680.10  5264.0 1681.54  5322.2 1682.67  5349.6 1682.89
#Mann=3,-1,0
  4547.7   0.035       0  5003.2   0.035       0  5007.2   0.035       0
Bank Sta=5003.2,5007.2
Exp/Cntr=0.3,0.1

Type RM Length L Ch R = 1,18588,63,63,63
BEGIN DESCRIPTION:
Mapping XS 3ea422c1
END DESCRIPTION:
XS GIS Cut Line= 4
      1643406.31      6946509.72      1643306.47      6946733.27
      1643221.84      6946791.86      1643106.93      6947093.23
#Sta/Elev= 30
  4659.3 1681.63  4674.3 1680.80  4690.3 1680.85  4697.5 1680.23  4756.0 1677.99
  4772.6 1677.97  4778.1 1677.44  4842.3 1676.09  4854.5 1674.88  4887.4 1674.92
  4899.7 1673.98  4922.7 1673.27  4937.6 1671.43  4952.4 1668.71  4966.7 1666.99
  4979.5 1666.19  4992.3 1666.12  4992.6 1665.62  4996.1 1665.62  4996.3 1666.12
  5007.1 1666.24  5010.3 1666.72  5015.6 1667.93  5035.0 1671.12  5040.3 1672.71
  5045.7 1673.75  5077.8 1676.31  5110.0 1677.53  5289.7 1681.16  5329.6 1681.64
#Mann=3,-1,0
  4659.3   0.035       0  4992.3   0.035       0  4996.3   0.035       0
Bank Sta=4992.3,4996.3
Exp/Cntr=0.3,0.1

Type RM Length L Ch R = 1,18525,45,45,45
BEGIN DESCRIPTION:
Mapping XS 31dc9cca
END DESCRIPTION:
XS GIS Cut Line= 4
      1643362.89      6946429.47      1643269.58      6946694.21
      1643169.76      6946761.48      1643050.38      6947030.61
#Sta/Elev= 30
  4604.6 1683.77  4687.9 1679.76  4804.5 1676.62  4815.1 1676.05  4825.4 1674.52
  4825.7 1674.02  4829.4 1674.52  4853.1 1674.89  4858.4 1676.13  4868.1 1675.10
  4878.7 1676.97  4884.0 1678.72  4913.9 1678.57  4920.0 1676.72  4934.9 1678.86
  4941.0 1676.97  4949.9 1678.41  4955.9 1675.52  4963.2 1677.88  4976.9 1678.09
  4985.9 1677.25  4991.9 1678.17  4999.4 1677.00  5005.5 1674.94  5012.8 1677.39
  5023.8 1678.12  5035.0 1676.39  5058.2 1675.73  5128.0 1678.20  5300.1 1680.98
#Mann=3,-1,0
  4604.6   0.035       0  4825.4   0.035       0  4829.4   0.035       0
Bank Sta=4825.4,4829.4
Exp/Cntr=0.3,0.1

Type RM Length L Ch R = 1,18480,328,328,328
BEGIN DESCRIPTION:
Mapping XS 17577db0
END DESCRIPTION:
XS GIS Cut Line= 4
      1643297.80      6946386.04      1643217.50      6946644.29
      1643152.39      6946722.42      1642967.94      6947013.21
#Sta/Elev= 30
  4632.5 1683.32  4686.9 1681.25  4707.9 1679.87  4730.1 1679.06  4795.2 1677.32
  4802.1 1676.72  4822.5 1676.48  4833.5 1675.72  4854.5 1675.44  4875.4 1673.17
  4885.9 1674.54  4902.3 1672.42  4969.7 1670.19  4970.0 1669.69  4973.5 1669.69
  4973.7 1670.19  4992.6 1671.11  5004.6 1670.79  5022.5 1671.28  5028.4 1670.82
  5043.7 1671.97  5049.6 1672.02  5058.6 1674.69  5064.8 1675.17  5094.1 1676.61
  5129.7 1677.78  5165.2 1678.56  5295.5 1680.27  5319.1 1680.39  5349.0 1679.88
#Mann=3,-1,0
  4632.5   0.035       0  4969.7   0.035       0  4973.7   0.035       0
Bank Sta=4969.7,4973.7
Exp/Cntr=0.3,0.1

Type RM Length L Ch R = 1,18152,249,249,249
BEGIN DESCRIPTION:
Mapping XS 71bd5986
END DESCRIPTION:
XS GIS Cut Line= 3
      1643020.86      6946201.69      1642960.08      6946486.45
      1642913.35      6946924.39
#Sta/Elev= 30
  4710.3 1684.06  4718.1 1683.10  4727.0 1683.49  4737.2 1682.65  4756.1 1682.08
  4788.3 1680.10  4812.1 1679.12  4819.0 1678.39  4849.7 1677.04  4880.4 1675.00
  4890.6 1674.94  4900.8 1674.32  4911.1 1673.12  4941.7 1670.97  4962.2 1668.33
  4980.6 1667.24  4980.9 1666.74  4984.4 1666.74  4984.6 1667.24  5005.2 1668.18
  5023.1 1669.94  5063.4 1671.40  5097.5 1671.94  5174.0 1673.92  5224.3 1676.32
  5264.5 1676.77  5282.3 1677.72  5287.3 1677.60  5304.7 1678.36  5441.9 1678.59
#Mann=4,-1,0
  4710.3    0.07       0  4756.1   0.035       0  4980.6   0.035       0
  4984.6   0.035       0
Bank Sta=4980.6,4984.6
Exp/Cntr=0.3,0.1

Type RM Length L Ch R = 1,17903,246,246,246
BEGIN DESCRIPTION:
Mapping XS 4f12570f
END DESCRIPTION:
XS GIS Cut Line= 3
      1642843.77      6946123.60      1642725.71      6946441.31
      1642630.23      6947048.91
#Sta/Elev= 30
  4664.6 1681.72  4700.0 1681.07  4705.4 1680.55  4744.0 1680.18  4780.3 1678.45
  4829.3 1676.00  4846.5 1674.64  4907.2 1671.87  4962.6 1668.25  4968.0 1667.40
  4997.1 1666.31  4997.4 1665.81  5000.9 1665.81  5001.1 1666.31  5008.8 1666.42
  5030.6 1667.12  5038.0 1668.07  5071.0 1669.91  5111.5 1670.93  5168.2 1671.97
  5230.8 1672.65  5235.8 1672.27  5303.9 1673.34  5361.0 1675.41  5374.7 1675.38
  5455.7 1677.74  5496.3 1679.45  5536.7 1679.33  5597.4 1679.98  5618.6 1681.06
#Mann=5,-1,0
  4664.6   0.035       0  4780.3    0.07       0  4997.1    0.07       0
  5001.1    0.07       0  5008.8   0.035       0
Bank Sta=4997.1,5001.1
Exp/Cntr=0.3,0.1

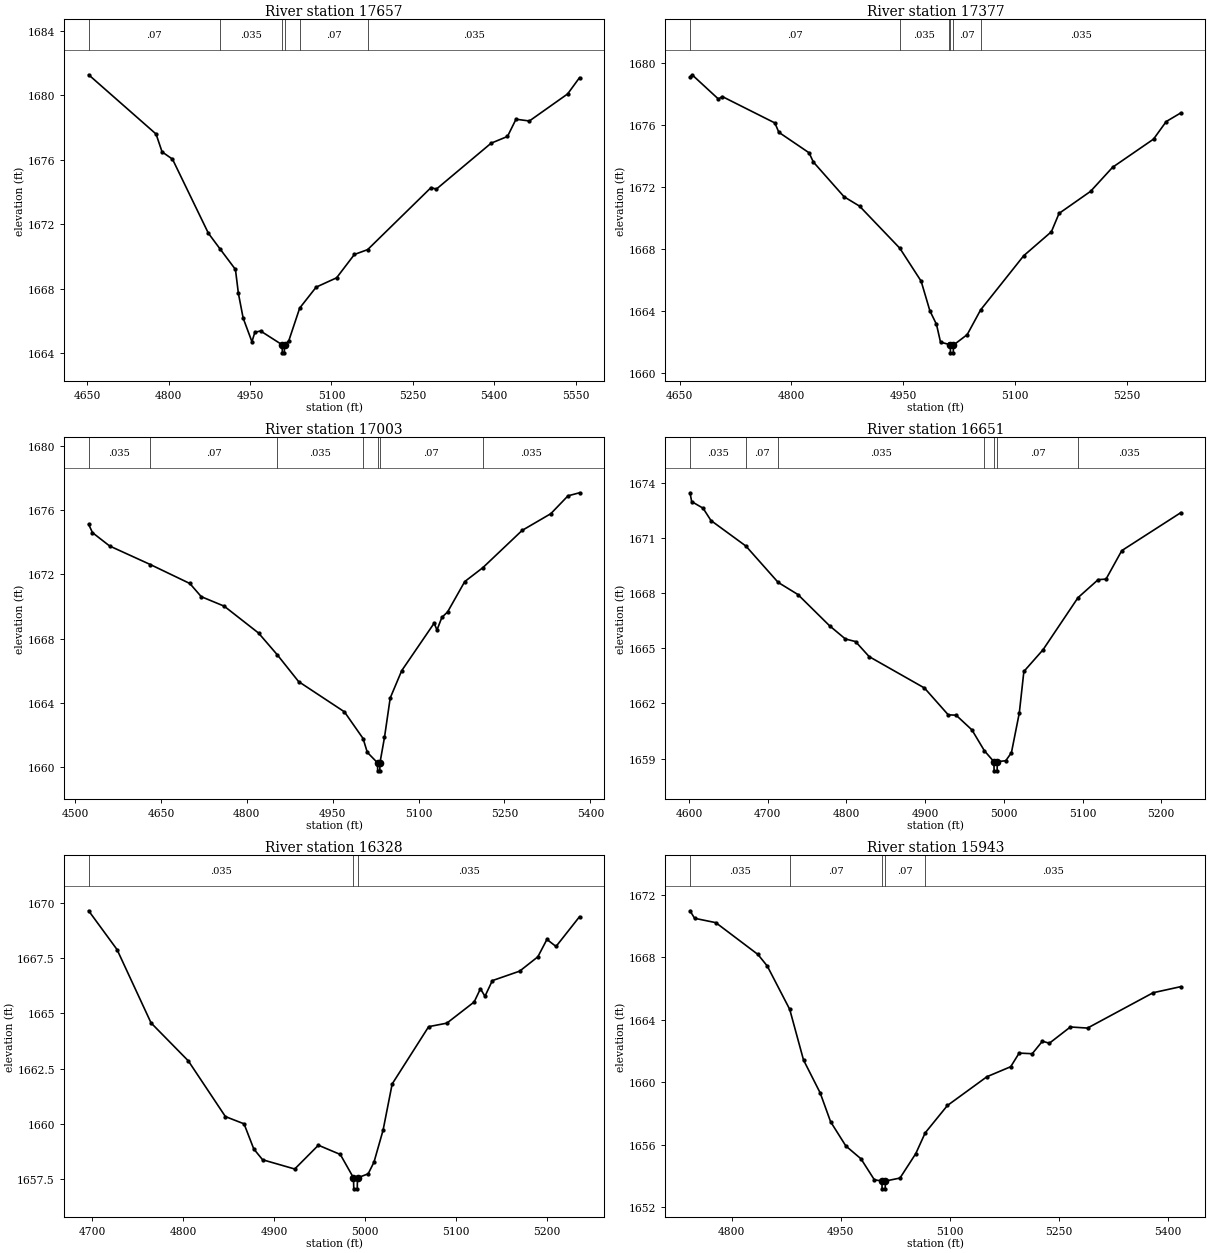
Type RM Length L Ch R = 1,17657,280,280,280
BEGIN DESCRIPTION:
Mapping XS 43525a76
END DESCRIPTION:
XS GIS Cut Line= 3
      1642364.94      6946131.24      1642486.47      6946457.63
      1642554.18      6947009.71
#Sta/Elev= 30
  4652.5 1681.28  4776.7 1677.60  4787.8 1676.49  4807.0 1676.04  4873.1 1671.44
  4894.7 1670.46  4923.0 1669.19  4928.4 1667.71  4937.2 1666.17  4953.4 1664.70
  4958.7 1665.28  4969.2 1665.37  5009.1 1664.51  5009.4 1664.01  5013.1 1664.01
  5013.4 1664.51  5021.3 1664.76  5041.4 1666.79  5071.7 1668.09  5109.4 1668.67
  5142.2 1670.12  5166.6 1670.42  5283.3 1674.27  5293.3 1674.18  5394.1 1677.03
  5424.3 1677.45  5440.0 1678.52  5464.6 1678.41  5535.1 1680.09  5557.0 1681.10
#Mann=6,-1,0
  4652.5    0.07       0  4894.7   0.035       0  5009.1   0.035       0
  5013.4   0.035       0  5041.4    0.07       0  5166.6   0.035       0
Bank Sta=5009.1,5013.4
Exp/Cntr=0.3,0.1

Type RM Length L Ch R = 1,17377,374,374,374
BEGIN DESCRIPTION:
Mapping XS 39332279
END DESCRIPTION:
XS GIS Cut Line= 3
      1642169.95      6946267.81      1642254.59      6946593.34
      1642328.80      6946907.13
#Sta/Elev= 30
  4664.0 1679.06  4666.8 1679.21  4702.1 1677.65  4707.3 1677.81  4777.9 1676.11
  4783.2 1675.51  4823.8 1674.19  4829.5 1673.60  4870.8 1671.36  4891.5 1670.76
  4945.6 1668.05  4974.2 1665.93  4985.9 1664.03  4994.8 1663.15  5000.2 1662.01
  5011.6 1661.86  5013.3 1661.82  5013.6 1661.32  5017.3 1661.32  5017.6 1661.82
  5036.0 1662.49  5054.0 1664.08  5111.9 1667.57  5149.0 1669.11  5159.3 1670.29
  5201.6 1671.71  5231.2 1673.26  5286.1 1675.07  5303.1 1676.20  5322.8 1676.76
#Mann=6,-1,0
  4664.0    0.07       0  4945.6   0.035       0  5011.6    0.07       0
  5013.3   0.035       0  5017.6    0.07       0  5054.0   0.035       0
Bank Sta=5013.3,5017.6
Exp/Cntr=0.3,0.1

Type RM Length L Ch R = 1,17003,352,352,352
BEGIN DESCRIPTION:
Mapping XS a8229e00
END DESCRIPTION:
XS GIS Cut Line= 3
      1641936.88      6946261.34      1641936.88      6946741.78
      1641916.05      6947118.07
#Sta/Elev= 30
  4523.7 1675.12  4530.4 1674.60  4560.4 1673.77  4631.3 1672.62  4700.4 1671.44
  4720.4 1670.62  4760.4 1670.03  4820.4 1668.36  4853.3 1667.00  4890.4 1665.34
  4970.4 1663.46  5003.0 1661.80  5010.4 1660.94  5028.2 1660.29  5028.5 1659.79
  5032.2 1659.79  5032.5 1660.29  5040.4 1661.87  5050.4 1664.32  5070.5 1666.02
  5127.1 1668.97  5132.1 1668.55  5140.6 1669.33  5150.6 1669.67  5180.6 1671.56
  5212.1 1672.42  5280.8 1674.74  5330.9 1675.78  5360.9 1676.89  5381.0 1677.08
#Mann=7,-1,0
  4523.7   0.035       0  4631.3    0.07       0  4853.3   0.035       0
  5003.0    0.07       0  5028.2   0.035       0  5032.5    0.07       0
  5212.1   0.035       0
Bank Sta=5028.2,5032.5
Exp/Cntr=0.3,0.1

Type RM Length L Ch R = 1,16651,323,323,323
BEGIN DESCRIPTION:
Mapping XS 4e2e36bf
END DESCRIPTION:
XS GIS Cut Line= 3
      1641640.25      6946391.50      1641601.19      6946790.79
      1641590.00      6947013.01
#Sta/Elev= 30
  4601.2 1673.47  4603.3 1672.99  4617.8 1672.63  4627.8 1671.96  4672.2 1670.57
  4713.2 1668.59  4738.3 1667.93  4778.5 1666.23  4798.6 1665.51  4811.5 1665.37
  4828.8 1664.55  4899.1 1662.84  4929.3 1661.38  4939.3 1661.36  4959.4 1660.56
  4975.3 1659.42  4987.3 1658.83  4987.6 1658.33  4991.4 1658.33  4991.7 1658.83
  5002.4 1658.88  5009.6 1659.32  5019.6 1661.48  5025.4 1663.74  5049.7 1664.92
  5094.2 1667.76  5119.8 1668.74  5129.8 1668.77  5149.8 1670.32  5224.9 1672.39
#Mann=7,-1,0
  4601.2   0.035       0  4672.2    0.07       0  4713.2   0.035       0
  4975.3    0.07       0  4987.3    0.07       0  4991.7    0.07       0
  5094.2   0.035       0
Bank Sta=4987.3,4991.7
Exp/Cntr=0.3,0.1

Type RM Length L Ch R = 1,16328,385,385,385
BEGIN DESCRIPTION:
Mapping XS fff12c2e
END DESCRIPTION:
XS GIS Cut Line= 3
      1641356.00      6946440.80      1641293.50      6946741.57
      1641287.01      6946973.78
#Sta/Elev= 30
  4696.0 1669.66  4727.2 1667.90  4764.6 1664.57  4805.5 1662.85  4846.3 1660.32
  4866.8 1659.99  4877.5 1658.85  4887.2 1658.36  4922.5 1657.94  4948.5 1659.02
  4972.6 1658.60  4987.1 1657.54  4987.4 1657.04  4991.2 1657.04  4991.5 1657.54
  5003.2 1657.72  5009.6 1658.25  5019.6 1659.70  5029.6 1661.80  5069.7 1664.40
  5089.7 1664.56  5119.7 1665.52  5126.6 1666.12  5131.6 1665.78  5139.7 1666.49
  5169.7 1666.92  5189.7 1667.57  5199.7 1668.36  5209.7 1668.04  5235.5 1669.39
#Mann=3,-1,0
  4696.0   0.035       0  4987.1   0.035       0  4991.5   0.035       0
Bank Sta=4987.1,4991.5
Exp/Cntr=0.3,0.1

Type RM Length L Ch R = 1,15943,438,438,438
BEGIN DESCRIPTION:
Mapping XS 25dd3b95
END DESCRIPTION:
XS GIS Cut Line= 3
      1640789.61      6946443.42      1640944.54      6946649.12
      1641110.01      6947033.06
#Sta/Elev= 30
  4742.7 1670.97  4749.0 1670.49  4778.2 1670.21  4836.1 1668.18  4849.0 1667.44
  4879.9 1664.67  4898.9 1661.43  4921.8 1659.33  4936.2 1657.48  4957.2 1655.93
  4978.0 1655.11  4996.4 1653.77  5006.8 1653.69  5007.1 1653.19  5011.3 1653.19
  5011.7 1653.69  5031.7 1653.88  5053.4 1655.44  5066.4 1656.77  5097.0 1658.52
  5151.4 1660.36  5184.1 1661.00  5195.7 1661.87  5213.7 1661.83  5227.7 1662.63
  5237.3 1662.50  5266.2 1663.54  5289.8 1663.47  5380.1 1665.73  5418.3 1666.12
#Mann=5,-1,0
  4742.7   0.035       0  4879.9    0.07       0  5006.8    0.07       0
  5011.7    0.07       0  5066.4   0.035       0
Bank Sta=5006.8,5011.7
Exp/Cntr=0.3,0.1

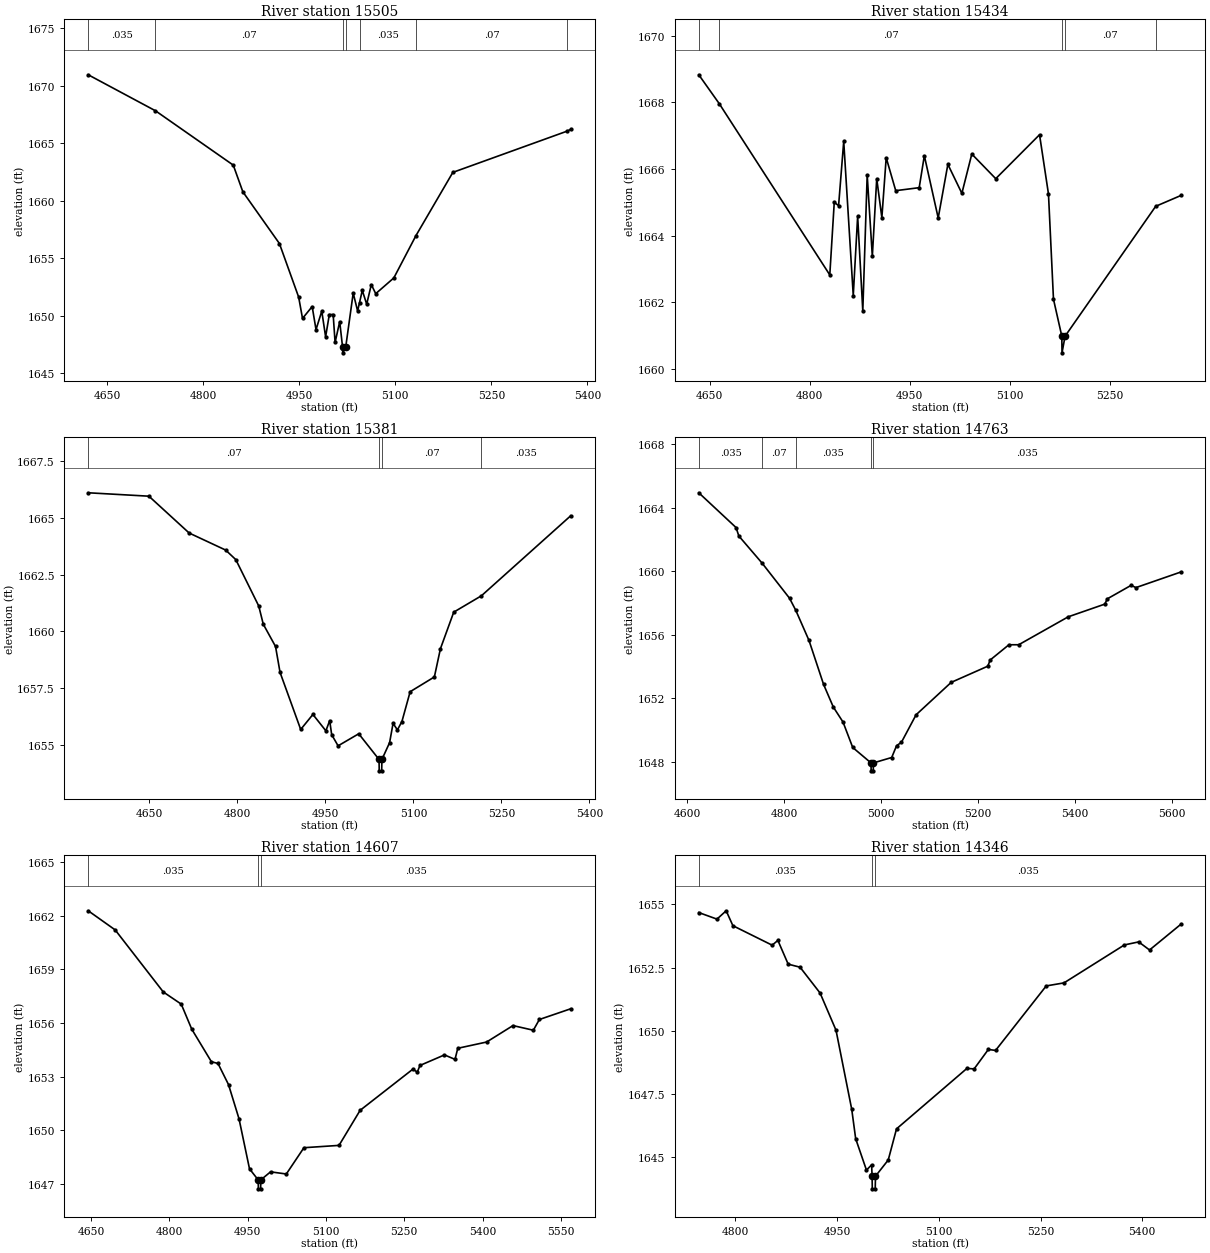
Type RM Length L Ch R = 1,15505,71,71,71
BEGIN DESCRIPTION:
Mapping XS fd0aab95
END DESCRIPTION:
XS GIS Cut Line= 4
      1640507.04      6946606.17      1640525.27      6946766.31
      1640646.36      6946948.60      1640904.15      6947219.40
#Sta/Elev= 30
  4620.2 1670.95  4725.3 1667.82  4846.8 1663.10  4861.8 1660.78  4918.9 1656.29
  4949.0 1651.63  4955.0 1649.78  4970.1 1650.81  4976.1 1648.81  4985.1 1650.41
  4991.1 1648.18  4996.9 1650.12  5002.9 1650.12  5005.9 1647.69  5013.1 1649.50
  5017.6 1647.29  5017.9 1646.79  5022.5 1647.29  5034.2 1651.98  5041.1 1650.43
  5044.1 1651.16  5048.4 1652.21  5055.3 1651.02  5062.5 1652.72  5069.4 1651.93
  5097.7 1653.30  5132.3 1656.98  5189.9 1662.47  5368.8 1666.06  5374.1 1666.21
#Mann=7,-1,0
  4620.2   0.035       0  4725.3    0.07       0  5017.6    0.07       0
  5022.5    0.07       0  5044.1   0.035       0  5132.3    0.07       0
  5368.8   0.035       0
Bank Sta=5017.6,5022.5
Exp/Cntr=0.3,0.1

Type RM Length L Ch R = 1,15434,53,53,53
BEGIN DESCRIPTION:
Mapping XS 32264fc0
END DESCRIPTION:
XS GIS Cut Line= 3
      1640358.58      6946718.11      1640596.88      6946999.38
      1640797.42      6947292.38
#Sta/Elev= 30
  4633.8 1668.83  4664.6 1667.96  4830.3 1662.82  4837.0 1665.00  4843.5 1664.90
  4851.2 1666.83  4865.5 1662.20  4872.1 1664.58  4879.8 1661.74  4886.4 1665.82
  4894.1 1663.38  4900.7 1665.71  4908.4 1664.54  4914.9 1666.34  4929.2 1665.35
  4964.4 1665.44  4972.1 1666.40  4992.9 1664.53  5007.4 1666.14  5028.4 1665.27
  5043.3 1666.45  5079.2 1665.71  5144.9 1667.03  5158.3 1665.25  5165.8 1662.09
  5178.3 1660.98  5178.6 1660.48  5183.2 1660.98  5319.1 1664.88  5357.5 1665.21
#Mann=5,-1,0
  4633.8   0.035       0  4664.6    0.07       0  5178.3    0.07       0
  5183.2    0.07       0  5319.1   0.035       0
Bank Sta=5178.3,5183.2
Exp/Cntr=0.3,0.1

Type RM Length L Ch R = 1,15381,618,618,618
BEGIN DESCRIPTION:
Mapping XS 78956871
END DESCRIPTION:
XS GIS Cut Line= 6
      1640195.84      6946783.23      1640425.01      6946876.98
      1640534.38      6947007.19      1640557.82      6947035.84
      1640599.49      6947106.15      1640669.75      6947383.28
#Sta/Elev= 30
  4545.8 1666.10  4649.2 1665.95  4717.8 1664.33  4780.0 1663.58  4797.3 1663.16
  4836.4 1661.12  4844.1 1660.32  4865.0 1659.34  4872.7 1658.20  4907.9 1655.69
  4928.7 1656.35  4950.8 1655.63  4957.3 1656.08  4960.7 1655.46  4971.6 1654.97
  5006.8 1655.50  5041.4 1654.37  5041.7 1653.87  5045.9 1653.87  5046.3 1654.37
  5059.4 1655.11  5065.3 1655.96  5072.7 1655.67  5080.4 1656.04  5094.4 1657.35
  5135.7 1658.00  5146.0 1659.24  5168.7 1660.85  5215.9 1661.57  5368.1 1665.09
#Mann=4,-1,0
  4545.8    0.07       0  5041.4    0.07       0  5046.3    0.07       0
  5215.9   0.035       0
Bank Sta=5041.4,5046.3
Exp/Cntr=0.3,0.1

Type RM Length L Ch R = 1,14763,156,156,156
BEGIN DESCRIPTION:
Mapping XS 9126c9d5
END DESCRIPTION:
XS GIS Cut Line= 3
      1640013.55      6946961.32      1640043.06      6947341.48
      1640119.45      6947950.81
#Sta/Elev= 30
  4623.6 1664.95  4700.5 1662.76  4706.2 1662.23  4754.5 1660.51  4810.8 1658.31
  4823.7 1657.55  4851.0 1655.65  4881.1 1652.88  4901.1 1651.46  4921.2 1650.51
  4941.2 1648.91  4978.9 1647.94  4979.2 1647.44  4983.5 1647.44  4983.9 1647.94
  5021.6 1648.28  5031.6 1649.02  5041.7 1649.24  5071.9 1650.97  5144.3 1653.01
  5219.8 1654.03  5224.8 1654.42  5263.4 1655.38  5283.6 1655.38  5385.8 1657.14
  5461.3 1657.94  5466.3 1658.27  5515.4 1659.12  5525.5 1658.98  5619.0 1659.97
#Mann=5,-1,0
  4623.6   0.035       0  4754.5    0.07       0  4823.7   0.035       0
  4978.9   0.035       0  4983.9   0.035       0
Bank Sta=4978.9,4983.9
Exp/Cntr=0.3,0.1

Type RM Length L Ch R = 1,14607,261,261,261
BEGIN DESCRIPTION:
Mapping XS 8c1c0d4f
END DESCRIPTION:
XS GIS Cut Line= 3
      1639864.59      6947040.92      1639902.79      6947396.86
      1639979.17      6947957.59
#Sta/Elev= 30
  4644.9 1662.27  4696.5 1661.20  4788.6 1657.73  4823.0 1657.05  4843.1 1655.65
  4880.7 1653.83  4893.4 1653.73  4913.5 1652.55  4933.6 1650.64  4953.7 1647.84
  4970.3 1647.22  4970.7 1646.72  4975.0 1646.72  4975.3 1647.22  4994.0 1647.67
  5024.2 1647.55  5057.9 1649.02  5125.1 1649.15  5165.5 1651.11  5266.4 1653.41
  5275.0 1653.25  5280.1 1653.62  5327.0 1654.21  5347.2 1653.96  5352.5 1654.58
  5407.7 1654.93  5458.2 1655.85  5497.2 1655.59  5508.7 1656.19  5568.8 1656.79
#Mann=3,-1,0
  4644.9   0.035       0  4970.3   0.035       0  4975.3   0.035       0
Bank Sta=4970.3,4975.3
Exp/Cntr=0.3,0.1

Type RM Length L Ch R = 1,14346,334,334,334
BEGIN DESCRIPTION:
Mapping XS 9f1f5b3f
END DESCRIPTION:
XS GIS Cut Line= 3
      1639598.34      6947310.92      1639700.77      6947548.76
      1639844.86      6947977.54
#Sta/Elev= 30
  4746.2 1654.68  4773.0 1654.42  4786.6 1654.75  4796.5 1654.16  4854.4 1653.39
  4862.8 1653.58  4878.0 1652.64  4895.5 1652.52  4925.0 1651.50  4948.5 1650.03
  4971.7 1646.90  4977.5 1645.74  4993.4 1644.50  5001.0 1644.71  5001.7 1644.26
  5002.0 1643.76  5006.3 1643.76  5006.7 1644.26  5025.5 1644.90  5037.7 1646.13
  5141.5 1648.52  5152.1 1648.50  5173.1 1649.27  5183.7 1649.23  5258.4 1651.78
  5284.6 1651.90  5373.6 1653.40  5394.7 1653.52  5410.7 1653.20  5457.5 1654.23
#Mann=3,-1,0
  4746.2   0.035       0  5001.7   0.035       0  5006.7   0.035       0
Bank Sta=5001.7,5006.7
Exp/Cntr=0.3,0.1

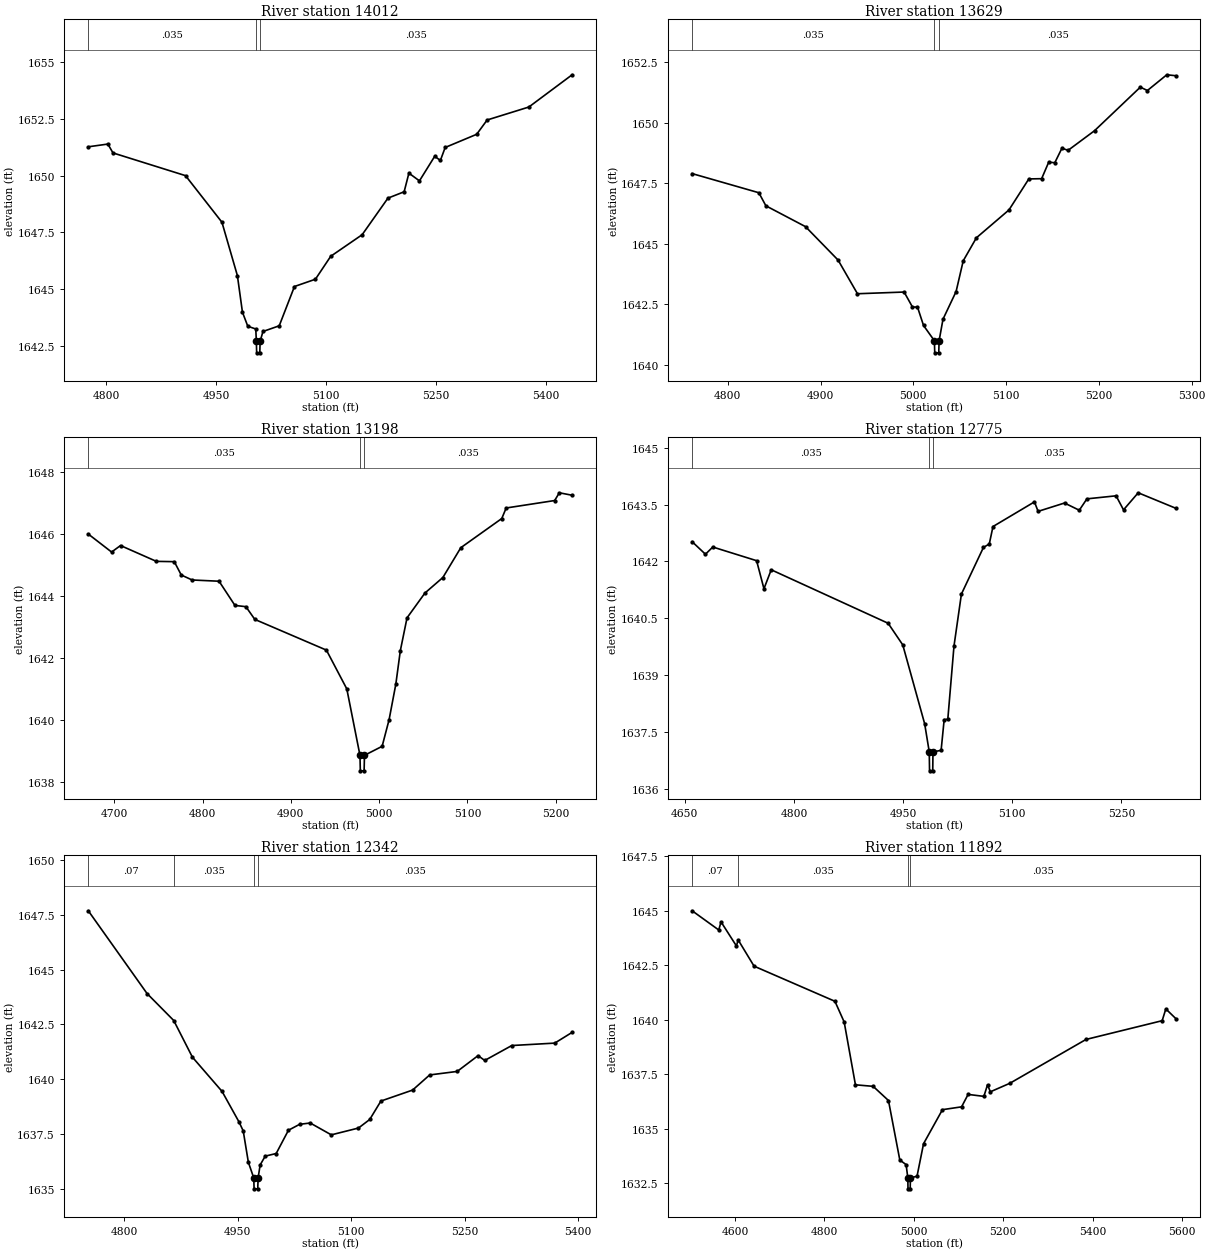
Type RM Length L Ch R = 1,14012,383,383,383
BEGIN DESCRIPTION:
Mapping XS 514c333d
END DESCRIPTION:
XS GIS Cut Line= 3
      1639339.44      6947635.85      1639495.69      6947799.70
      1639773.10      6948133.45
#Sta/Elev= 30
  4775.6 1651.27  4802.3 1651.39  4809.3 1651.00  4908.3 1650.00  4958.0 1647.95
  4979.1 1645.60  4986.0 1643.99  4993.3 1643.37  5004.2 1643.25  5005.0 1642.70
  5005.4 1642.20  5009.7 1642.20  5010.1 1642.70  5014.0 1643.14  5036.2 1643.39
  5057.0 1645.12  5085.6 1645.44  5106.5 1646.45  5149.4 1647.40  5184.6 1649.01
  5206.7 1649.29  5213.2 1650.11  5227.6 1649.77  5248.4 1650.85  5256.2 1650.67
  5262.7 1651.24  5305.7 1651.82  5320.0 1652.45  5376.9 1653.02  5436.0 1654.44
#Mann=3,-1,0
  4775.6   0.035       0  5005.0   0.035       0  5010.1   0.035       0
Bank Sta=5005,5010.1
Exp/Cntr=0.3,0.1

Type RM Length L Ch R = 1,13629,431,431,431
BEGIN DESCRIPTION:
Mapping XS 3e540148
END DESCRIPTION:
XS GIS Cut Line= 3
      1639181.15      6947979.85      1639360.15      6948136.07
      1639575.02      6948321.64
#Sta/Elev= 30
  4761.6 1647.90  4833.5 1647.11  4841.1 1646.57  4883.8 1645.71  4918.9 1644.33
  4939.8 1642.94  4990.1 1643.01  4999.1 1642.39  5004.5 1642.39  5011.0 1641.63
  5022.7 1641.00  5023.1 1640.50  5027.4 1640.50  5027.8 1641.00  5032.0 1641.89
  5046.1 1643.03  5053.8 1644.30  5068.0 1645.25  5103.1 1646.40  5124.5 1647.68
  5138.3 1647.69  5145.9 1648.37  5152.5 1648.35  5160.2 1648.95  5166.8 1648.86
  5195.3 1649.67  5244.7 1651.47  5252.3 1651.33  5273.2 1651.98  5283.1 1651.94
#Mann=3,-1,0
  4761.6   0.035       0  5022.7   0.035       0  5027.8   0.035       0
Bank Sta=5022.7,5027.8
Exp/Cntr=0.3,0.1

Type RM Length L Ch R = 1,13198,423,423,423
BEGIN DESCRIPTION:
Mapping XS e6be4aaa
END DESCRIPTION:
XS GIS Cut Line= 3
      1639042.22      6948121.96      1639096.48      6948447.48
      1639133.37      6948662.32
#Sta/Elev= 30
  4670.6 1645.99  4697.0 1645.41  4707.1 1645.62  4747.7 1645.11  4768.0 1645.10
  4775.9 1644.67  4788.2 1644.51  4818.7 1644.47  4836.7 1643.69  4849.1 1643.65
  4859.2 1643.24  4940.3 1642.25  4963.4 1641.00  4978.3 1638.86  4978.7 1638.36
  4983.0 1638.36  4983.4 1638.86  5003.4 1639.15  5011.3 1640.01  5018.9 1641.15
  5024.0 1642.23  5031.6 1643.29  5051.9 1644.09  5072.2 1644.59  5092.5 1645.55
  5138.9 1646.49  5143.9 1646.83  5198.8 1647.07  5204.1 1647.32  5218.6 1647.24
#Mann=3,-1,0
  4670.6   0.035       0  4978.3   0.035       0  4983.4   0.035       0
Bank Sta=4978.3,4983.4
Exp/Cntr=0.3,0.1

Type RM Length L Ch R = 1,12775,433,433,433
BEGIN DESCRIPTION:
Mapping XS 74ddc5f7
END DESCRIPTION:
XS GIS Cut Line= 3
      1638750.56      6948249.74      1638719.09      6948590.50
      1638770.05      6948909.24
#Sta/Elev= 30
  4660.1 1642.52  4678.4 1642.19  4688.5 1642.38  4748.7 1642.02  4758.8 1641.28
  4768.8 1641.78  4929.5 1640.37  4949.6 1639.80  4979.7 1637.72  4986.0 1636.98
  4986.4 1636.48  4990.8 1636.48  4991.1 1636.98  5002.3 1637.02  5006.5 1637.83
  5011.5 1637.84  5020.0 1639.77  5030.2 1641.14  5060.5 1642.37  5068.5 1642.46
  5073.6 1642.92  5130.6 1643.57  5135.6 1643.32  5171.9 1643.54  5192.2 1643.35
  5202.7 1643.65  5242.8 1643.73  5253.0 1643.36  5273.2 1643.81  5325.1 1643.40
#Mann=3,-1,0
  4660.1   0.035       0  4986.0   0.035       0  4991.1   0.035       0
Bank Sta=4986,4991.1
Exp/Cntr=0.3,0.1

Type RM Length L Ch R = 1,12342,450,450,450
BEGIN DESCRIPTION:
Mapping XS e22e29c2
END DESCRIPTION:
XS GIS Cut Line= 3
      1638249.26      6948258.47      1638359.93      6948480.90
      1638582.30      6948803.06
#Sta/Elev= 30
  4752.4 1647.68  4830.1 1643.91  4865.4 1642.68  4890.1 1641.01  4929.3 1639.45
  4951.7 1638.06  4957.3 1637.65  4964.1 1636.22  4971.2 1635.51  4971.7 1635.01
  4976.5 1635.01  4977.0 1635.51  4979.7 1636.10  4986.4 1636.50  5000.9 1636.62
  5017.1 1637.68  5031.9 1637.95  5045.9 1638.01  5073.8 1637.47  5109.7 1637.78
  5124.6 1638.17  5139.4 1639.01  5181.3 1639.51  5203.9 1640.20  5240.3 1640.36
  5267.9 1641.08  5276.7 1640.86  5312.5 1641.54  5369.3 1641.65  5392.3 1642.14
#Mann=4,-1,0
  4752.4    0.07       0  4865.4   0.035       0  4971.2   0.035       0
  4977.0   0.035       0
Bank Sta=4971.2,4977
Exp/Cntr=0.3,0.1

Type RM Length L Ch R = 1,11892,473,473,473
BEGIN DESCRIPTION:
Mapping XS bdef1adc
END DESCRIPTION:
XS GIS Cut Line= 3
      1637892.97      6948290.03      1638025.34      6948769.59
      1638489.75      6949125.50
#Sta/Elev= 30
  4504.1 1644.99  4563.6 1644.11  4568.8 1644.48  4603.1 1643.38  4607.2 1643.65
  4642.7 1642.45  4823.6 1640.84  4844.3 1639.89  4869.5 1637.01  4909.1 1636.94
  4943.4 1636.29  4968.8 1633.56  4982.9 1633.35  4986.7 1632.74  4987.1 1632.24
  4992.0 1632.24  4992.5 1632.74  5007.3 1632.82  5021.9 1634.31  5064.2 1635.87
  5107.0 1636.00  5121.6 1636.57  5156.9 1636.48  5165.0 1637.01  5171.4 1636.69
  5215.0 1637.08  5385.4 1639.09  5555.8 1639.95  5564.0 1640.49  5586.7 1640.04
#Mann=4,-1,0
  4504.1    0.07       0  4607.2   0.035       0  4986.7   0.035       0
  4992.5   0.035       0
Bank Sta=4986.7,4992.5
Exp/Cntr=0.3,0.1

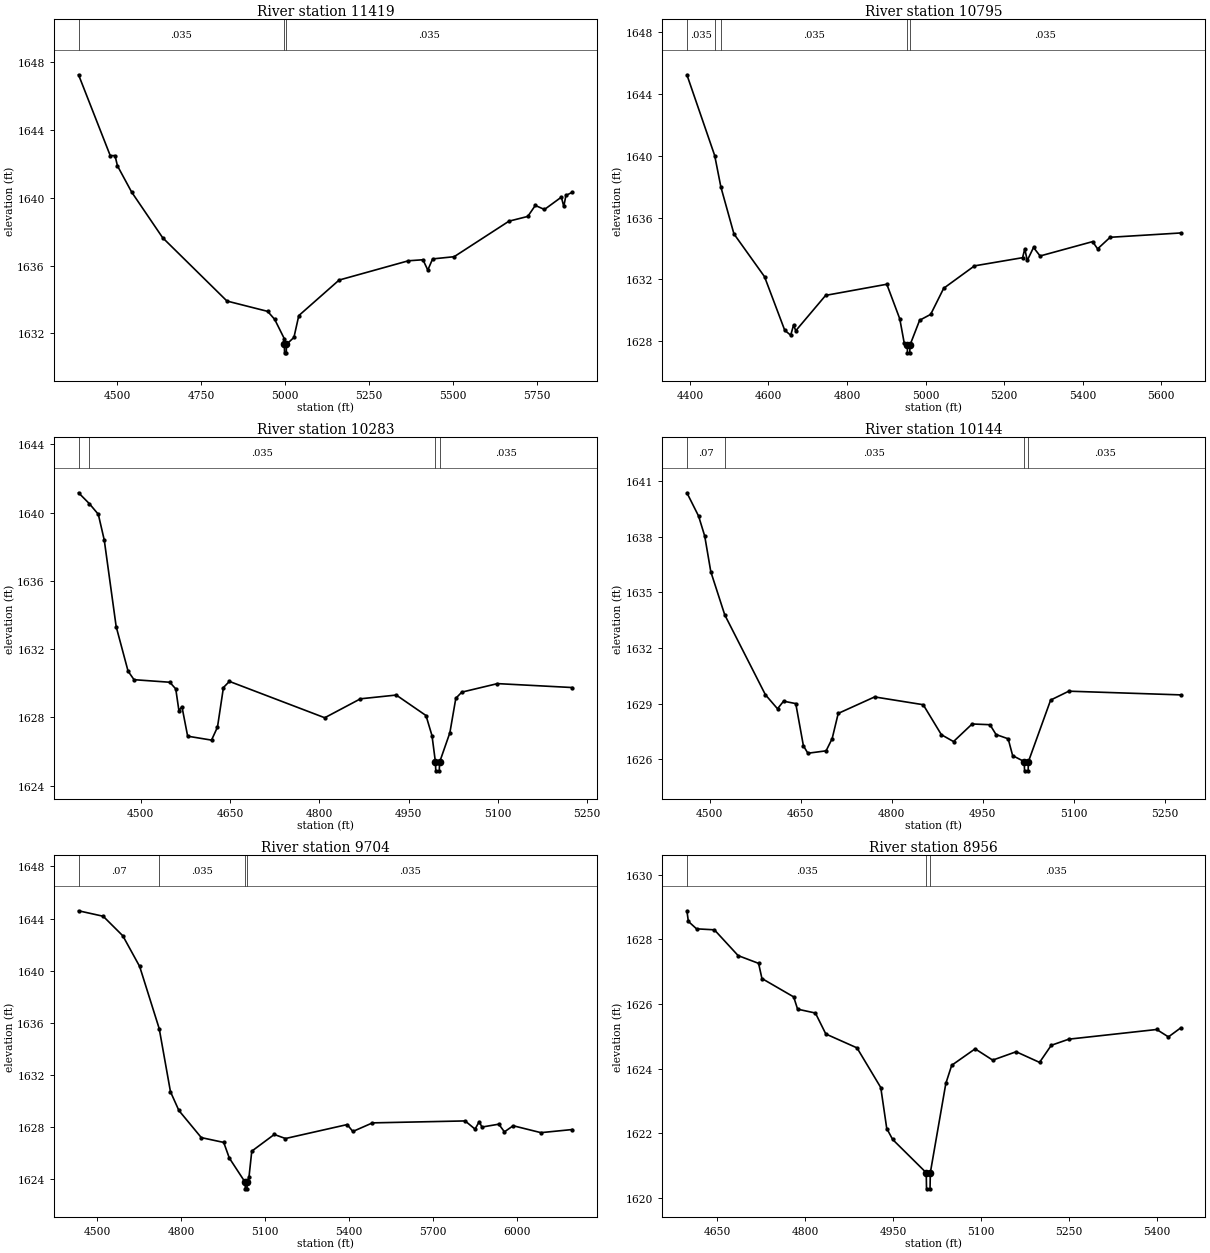
Type RM Length L Ch R = 1,11419,624,624,624
BEGIN DESCRIPTION:
Mapping XS b65cd89d
END DESCRIPTION:
XS GIS Cut Line= 3
      1637275.47      6948744.43      1637752.88      6949137.22
      1638420.65      6949668.40
#Sta/Elev= 30
  4384.2 1647.27  4478.5 1642.50  4492.9 1642.49  4500.1 1641.89  4542.4 1640.34
  4634.9 1637.64  4826.5 1633.90  4947.7 1633.29  4968.6 1632.82  4997.2 1631.68
  4997.5 1631.34  4998.0 1630.84  5003.2 1630.84  5003.7 1631.34  5026.0 1631.75
  5040.5 1633.04  5160.6 1635.14  5367.2 1636.28  5410.5 1636.34  5424.9 1635.73
  5439.3 1636.39  5503.4 1636.52  5666.8 1638.62  5722.8 1638.90  5745.3 1639.55
  5772.5 1639.31  5822.9 1640.04  5830.1 1639.49  5836.5 1640.14  5855.7 1640.33
#Mann=3,-1,0
  4384.2   0.035       0  4997.5   0.035       0  5003.7   0.035       0
Bank Sta=4997.5,5003.7
Exp/Cntr=0.3,0.1

Type RM Length L Ch R = 1,10795,512,512,512
BEGIN DESCRIPTION:
Mapping XS 50e8a494
END DESCRIPTION:
XS GIS Cut Line= 3
      1637110.22      6949070.27      1637375.83      6949615.37
      1637669.24      6950196.99
#Sta/Elev= 30
  4392.2 1645.25  4463.0 1640.02  4478.8 1637.98  4512.0 1634.95  4589.9 1632.18
  4641.4 1628.71  4656.6 1628.39  4663.9 1629.05  4669.5 1628.68  4745.6 1630.97
  4901.4 1631.69  4934.4 1629.45  4945.9 1627.86  4953.5 1627.75  4954.0 1627.25
  4959.9 1627.25  4960.4 1627.75  4985.0 1629.36  5013.1 1629.74  5046.3 1631.43
  5124.7 1632.88  5247.2 1633.41  5252.8 1633.98  5259.1 1633.23  5275.1 1634.07
  5291.8 1633.52  5425.6 1634.45  5438.3 1633.98  5470.2 1634.73  5650.0 1635.01
#Mann=5,-1,0
  4392.2   0.035       0  4463.0    0.07       0  4478.8   0.035       0
  4953.5   0.035       0  4960.4   0.035       0
Bank Sta=4953.5,4960.4
Exp/Cntr=0.3,0.1

Type RM Length L Ch R = 1,10283,139,139,139
BEGIN DESCRIPTION:
Mapping XS 59bba16c
END DESCRIPTION:
XS GIS Cut Line= 3
      1636977.61      6949184.85      1636950.26      6949791.59
      1636955.77      6950013.76
#Sta/Elev= 30
  4395.6 1641.16  4413.8 1640.52  4428.8 1639.90  4438.8 1638.39  4458.8 1633.32
  4478.8 1630.71  4488.8 1630.21  4548.9 1630.06  4558.9 1629.67  4564.2 1628.40
  4569.3 1628.63  4578.9 1626.90  4619.0 1626.67  4629.0 1627.43  4639.0 1629.75
  4649.0 1630.11  4809.2 1627.98  4869.2 1629.09  4929.3 1629.31  4979.3 1628.11
  4989.4 1626.93  4995.2 1625.37  4995.7 1624.87  5001.6 1624.87  5002.1 1625.37
  5019.4 1627.10  5029.4 1629.12  5039.4 1629.48  5099.4 1629.98  5225.2 1629.75
#Mann=4,-1,0
  4395.6    0.07       0  4413.8   0.035       0  4995.2   0.035       0
  5002.1   0.035       0
Bank Sta=4995.2,5002.1
Exp/Cntr=0.3,0.1

Type RM Length L Ch R = 1,10144,440,440,440
BEGIN DESCRIPTION:
Mapping XS 1dd1a3f4
END DESCRIPTION:
XS GIS Cut Line= 3
      1636803.13      6949218.66      1636822.66      6949757.73
      1636828.63      6950032.45
#Sta/Elev= 30
  4462.2 1640.38  4481.5 1639.12  4491.6 1638.04  4501.6 1636.12  4524.6 1633.79
  4591.6 1629.48  4611.6 1628.72  4621.6 1629.13  4641.7 1629.00  4654.3 1626.72
  4661.7 1626.32  4691.7 1626.45  4701.7 1627.11  4711.7 1628.47  4771.7 1629.36
  4851.8 1628.94  4881.8 1627.32  4901.8 1626.95  4932.5 1627.90  4961.9 1627.86
  4971.9 1627.33  4991.9 1627.10  4999.3 1626.19  5018.4 1625.87  5018.9 1625.37
  5024.8 1625.37  5025.3 1625.87  5061.9 1629.19  5091.9 1629.67  5276.4 1629.47
#Mann=4,-1,0
  4462.2    0.07       0  4524.6   0.035       0  5018.4   0.035       0
  5025.3   0.035       0
Bank Sta=5018.4,5025.3
Exp/Cntr=0.3,0.1

Type RM Length L Ch R = 1,9704,748,748,748
BEGIN DESCRIPTION:
Mapping XS 235fcf4a
END DESCRIPTION:
XS GIS Cut Line= 3
      1636497.71      6949020.09      1636465.89      6949589.76
      1636556.30      6950780.07
#Sta/Elev= 30
  4433.1 1644.60  4521.1 1644.18  4591.3 1642.68  4651.4 1640.33  4721.3 1635.56
  4761.5 1630.72  4791.6 1629.28  4871.7 1627.20  4951.8 1626.83  4971.8 1625.63
  5028.5 1623.77  5029.0 1623.27  5035.0 1623.27  5035.5 1623.77  5042.0 1624.16
  5052.0 1626.16  5132.3 1627.44  5172.4 1627.13  5393.0 1628.20  5413.1 1627.67
  5483.3 1628.33  5814.2 1628.48  5849.7 1627.85  5864.4 1628.42  5874.4 1628.01
  5934.6 1628.23  5954.6 1627.64  5985.9 1628.11  6085.0 1627.58  6197.4 1627.82
#Mann=4,-1,0
  4433.1    0.07       0  4721.3   0.035       0  5028.5   0.035       0
  5035.5   0.035       0
Bank Sta=5028.5,5035.5
Exp/Cntr=0.3,0.1

Type RM Length L Ch R = 1,8956,337,337,337
BEGIN DESCRIPTION:
Mapping XS d533310c
END DESCRIPTION:
XS GIS Cut Line= 3
      1635870.65      6949341.78      1635801.65      6949742.79
      1635797.74      6950178.97
#Sta/Elev= 30
  4598.0 1628.89  4600.5 1628.56  4614.5 1628.33  4644.9 1628.30  4685.5 1627.50
  4720.4 1627.26  4726.1 1626.79  4780.3 1626.22  4787.0 1625.84  4817.4 1625.72
  4835.2 1625.07  4888.4 1624.64  4929.0 1623.41  4939.2 1622.14  4949.3 1621.80
  5006.6 1620.77  5007.1 1620.27  5013.1 1620.27  5013.6 1620.77  5040.1 1623.54
  5050.1 1624.10  5090.1 1624.61  5120.1 1624.26  5160.1 1624.52  5200.1 1624.19
  5220.1 1624.72  5250.1 1624.91  5400.1 1625.21  5420.1 1624.98  5441.1 1625.26
#Mann=3,-1,0
  4598.0   0.035       0  5006.6   0.035       0  5013.6   0.035       0
Bank Sta=5006.6,5013.6
Exp/Cntr=0.3,0.1