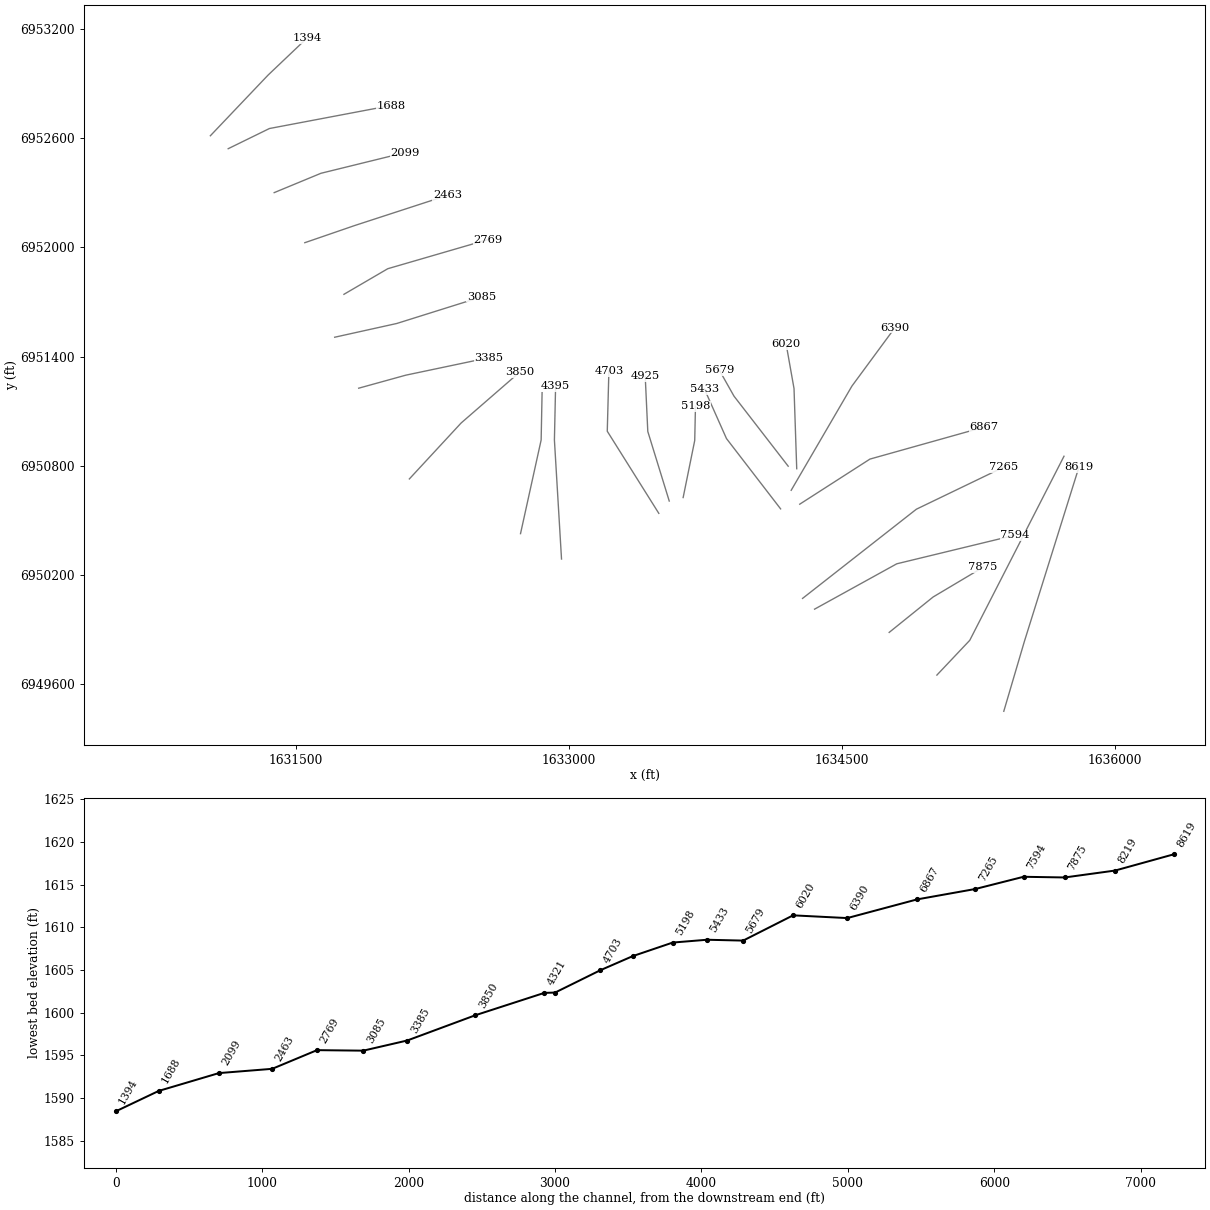
HEC-RAS study Chimney Creek 1105.prj: Chimney Creek 1105 Base Level Engineering

--- Chimney Creek 1105.g01 (geometry) --- (continued)

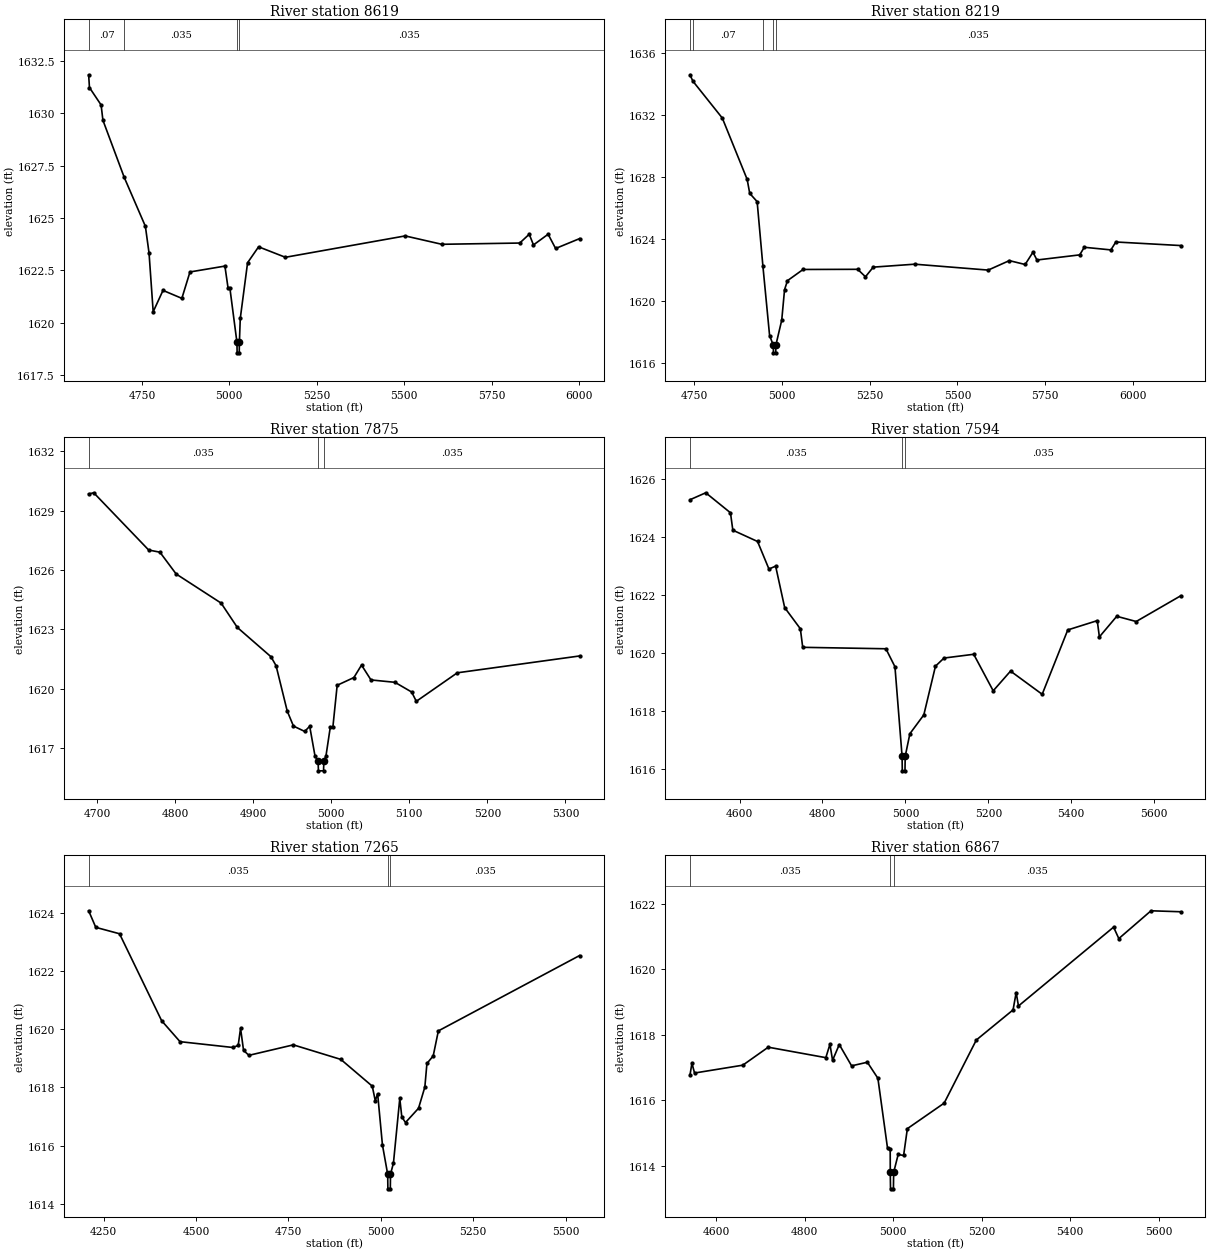
Type RM Length L Ch R = 1,8619,400,400,400
BEGIN DESCRIPTION:
Mapping XS 35ea16b7
END DESCRIPTION:
XS GIS Cut Line= 3
      1635388.87      6949452.39      1635502.17      6949836.54
      1635801.87      6950793.71
#Sta/Elev= 30
  4597.8 1631.84  4600.1 1631.23  4633.4 1630.40  4638.6 1629.67  4699.6 1626.94
  4760.0 1624.61  4770.5 1623.33  4782.3 1620.53  4810.4 1621.55  4864.3 1621.17
  4887.5 1622.43  4987.4 1622.71  4996.5 1621.65  5001.7 1621.65  5021.8 1619.07
  5022.3 1618.57  5028.3 1618.57  5028.8 1619.07  5031.3 1620.21  5052.2 1622.87
  5083.7 1623.63  5160.3 1623.13  5502.8 1624.15  5607.6 1623.75  5830.3 1623.81
  5857.5 1624.23  5869.6 1623.72  5911.5 1624.23  5932.9 1623.55  6001.3 1624.02
#Mann=4,-1,0
  4597.8    0.07       0  4699.6   0.035       0  5021.8   0.035       0
  5028.8   0.035       0
Bank Sta=5021.8,5028.8
Exp/Cntr=0.3,0.1

Type RM Length L Ch R = 1,8219,344,344,344
BEGIN DESCRIPTION:
Mapping XS edea0989
END DESCRIPTION:
XS GIS Cut Line= 3
      1635021.35      6949651.13      1635201.91      6949842.10
      1635719.59      6950852.93
#Sta/Elev= 30
  4737.9 1634.58  4746.1 1634.17  4830.0 1631.79  4900.8 1627.84  4908.1 1626.94
  4929.2 1626.41  4945.7 1622.24  4964.7 1617.78  4975.2 1617.17  4975.7 1616.67
  4982.1 1616.67  4982.6 1617.17  4999.3 1618.78  5007.3 1620.74  5015.7 1621.32
  5060.1 1622.04  5215.6 1622.05  5237.8 1621.57  5260.0 1622.19  5378.1 1622.38
  5587.4 1622.00  5647.7 1622.61  5692.7 1622.36  5715.0 1623.15  5726.4 1622.65
  5848.2 1622.98  5861.2 1623.47  5937.0 1623.30  5951.1 1623.81  6136.4 1623.58
#Mann=5,-1,0
  4737.9   0.035       0  4746.1    0.07       0  4945.7   0.035       0
  4975.2   0.035       0  4982.6   0.035       0
Bank Sta=4975.2,4982.6
Exp/Cntr=0.3,0.1

Type RM Length L Ch R = 1,7875,281,281,281
BEGIN DESCRIPTION:
Mapping XS 3bf5cc23
END DESCRIPTION:
XS GIS Cut Line= 3
      1634759.20      6949885.50      1635000.52      6950079.95
      1635274.66      6950243.05
#Sta/Elev= 30
  4689.2 1629.84  4695.7 1629.90  4766.1 1627.01  4780.5 1626.90  4801.3 1625.80
  4858.9 1624.33  4879.7 1623.10  4922.8 1621.62  4929.3 1621.17  4943.6 1618.88
  4951.6 1618.12  4966.0 1617.85  4972.4 1618.11  4979.2 1616.61  4983.1 1616.36
  4983.6 1615.86  4990.1 1615.86  4990.6 1616.36  4993.2 1616.60  4998.8 1618.07
  5002.1 1618.07  5007.6 1620.18  5029.0 1620.57  5038.8 1621.20  5050.9 1620.45
  5081.6 1620.33  5103.0 1619.84  5109.0 1619.37  5161.5 1620.81  5318.1 1621.66
#Mann=3,-1,0
  4689.2   0.035       0  4983.1   0.035       0  4990.6   0.035       0
Bank Sta=4983.1,4990.6
Exp/Cntr=0.3,0.1

Type RM Length L Ch R = 1,7594,329,329,329
BEGIN DESCRIPTION:
Mapping XS 80943923
END DESCRIPTION:
XS GIS Cut Line= 3
      1634349.33      6950013.20      1634800.86      6950262.24
      1635450.03      6950419.46
#Sta/Elev= 30
  4480.6 1625.29  4518.6 1625.53  4578.2 1624.84  4583.9 1624.24  4643.5 1623.85
  4671.0 1622.90  4687.1 1623.00  4708.9 1621.57  4746.7 1620.84  4752.4 1620.20
  4953.0 1620.15  4974.8 1619.53  4992.0 1616.44  4992.5 1615.94  4999.0 1615.94
  4999.5 1616.44  5010.8 1617.22  5044.4 1617.87  5072.5 1619.55  5093.1 1619.83
  5164.7 1619.96  5211.7 1618.70  5253.5 1619.38  5329.8 1618.58  5391.5 1620.80
  5462.6 1621.12  5467.7 1620.56  5509.6 1621.27  5556.5 1621.09  5664.2 1621.98
#Mann=3,-1,0
  4480.6   0.035       0  4992.0   0.035       0  4999.5   0.035       0
Bank Sta=4992,4999.5
Exp/Cntr=0.3,0.1

Type RM Length L Ch R = 1,7265,398,398,398
BEGIN DESCRIPTION:
Mapping XS 1526348a
END DESCRIPTION:
XS GIS Cut Line= 3
      1634283.36      6950072.22      1634908.76      6950562.18
      1635388.99      6950793.48
#Sta/Elev= 30
  4209.8 1624.07  4229.1 1623.50  4293.3 1623.28  4407.2 1620.29  4456.9 1619.57
  4599.8 1619.37  4614.2 1619.44  4620.6 1620.03  4628.7 1619.27  4643.2 1619.10
  4763.4 1619.46  4891.8 1618.96  4976.8 1618.04  4984.9 1617.54  4991.3 1617.78
  5004.3 1616.02  5018.5 1615.01  5019.0 1614.51  5025.6 1614.51  5026.1 1615.01
  5034.1 1615.40  5051.2 1617.62  5056.7 1616.98  5066.7 1616.79  5101.9 1617.28
  5119.0 1618.01  5124.6 1618.82  5141.6 1619.08  5155.5 1619.94  5537.3 1622.53
#Mann=3,-1,0
  4209.8   0.035       0  5018.5   0.035       0  5026.1   0.035       0
Bank Sta=5018.5,5026.1
Exp/Cntr=0.3,0.1

Type RM Length L Ch R = 1,6867,477,477,477
BEGIN DESCRIPTION:
Mapping XS ab8a299b
END DESCRIPTION:
XS GIS Cut Line= 3
      1634267.82      6950589.66      1634653.56      6950837.35
      1635279.98      6951012.99
#Sta/Elev= 30
  4541.1 1616.77  4545.5 1617.13  4551.4 1616.83  4660.4 1617.07  4717.9 1617.62
  4848.0 1617.30  4857.3 1617.71  4863.2 1617.22  4878.4 1617.70  4906.2 1617.05
  4941.8 1617.16  4965.6 1616.67  4987.4 1614.53  4993.4 1614.51  4993.6 1613.79
  4994.1 1613.29  5000.7 1613.29  5001.2 1613.79  5011.4 1614.34  5023.7 1614.31
  5032.2 1615.13  5115.3 1615.91  5188.0 1617.84  5271.0 1618.76  5278.0 1619.29
  5283.2 1618.88  5498.1 1621.29  5509.9 1620.94  5582.6 1621.79  5650.1 1621.76
#Mann=3,-1,0
  4541.1   0.035       0  4993.6   0.035       0  5001.2   0.035       0
Bank Sta=4993.6,5001.2
Exp/Cntr=0.3,0.1

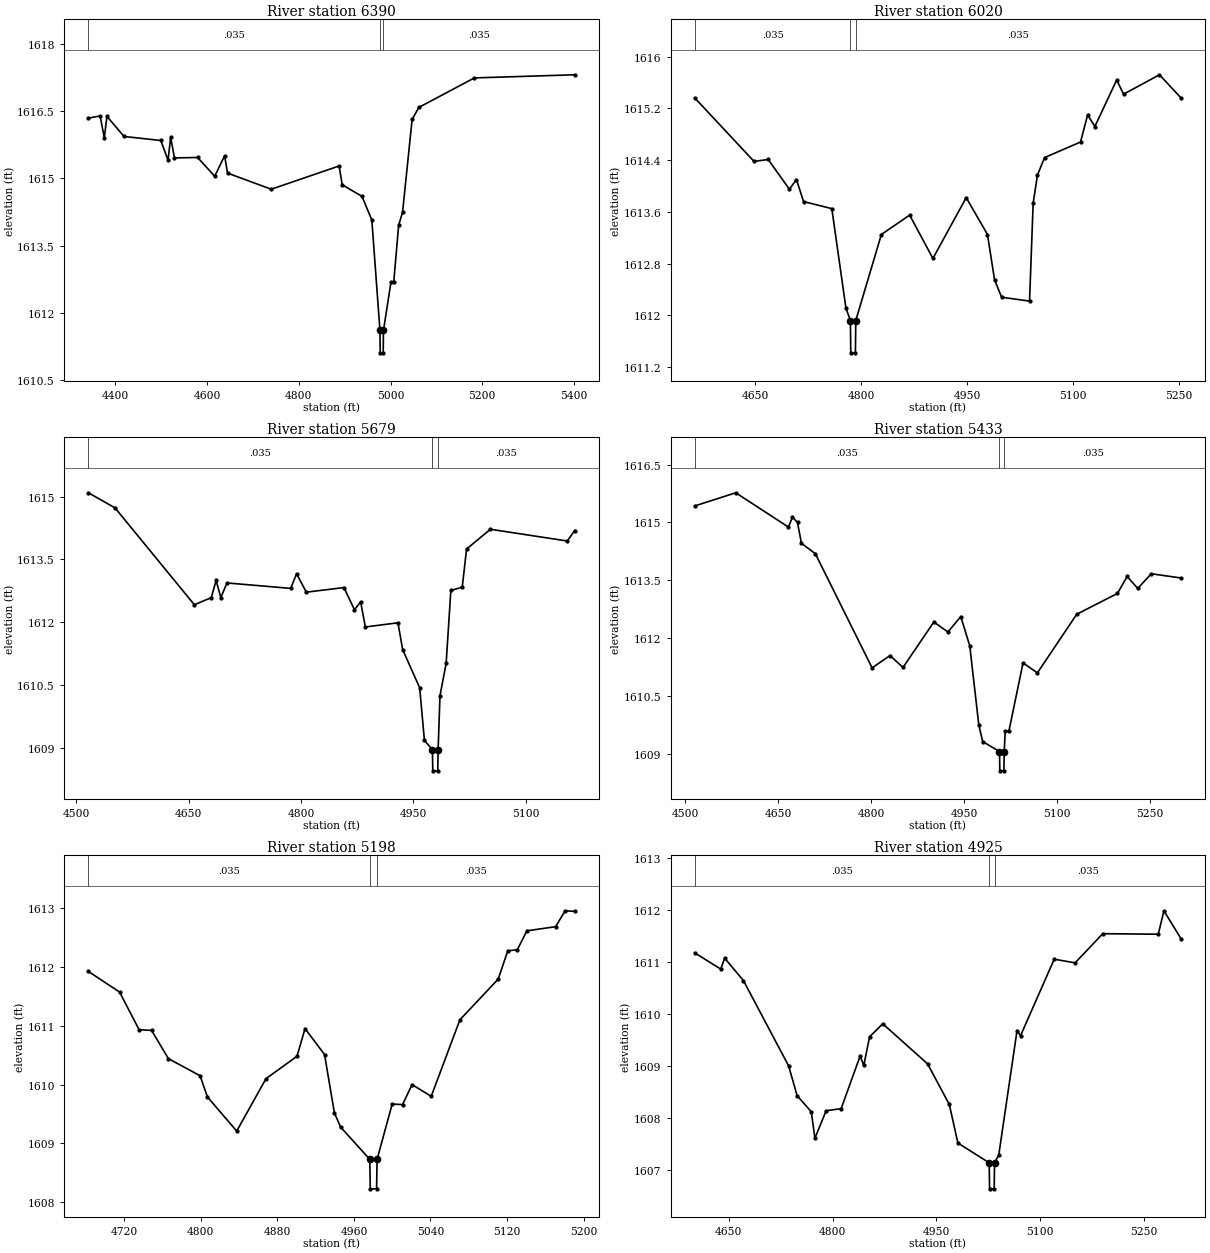
Type RM Length L Ch R = 1,6390,370,370,370
BEGIN DESCRIPTION:
Mapping XS ee3bbb00
END DESCRIPTION:
XS GIS Cut Line= 3
      1634220.90      6950666.00      1634554.60      6951238.39
      1634790.17      6951558.12
#Sta/Elev= 30
  4341.6 1616.35  4367.1 1616.40  4376.2 1615.91  4382.0 1616.39  4419.2 1615.94
  4499.4 1615.85  4515.1 1615.41  4520.9 1615.92  4529.1 1615.46  4579.6 1615.47
  4616.9 1615.05  4638.4 1615.51  4644.9 1615.12  4740.1 1614.76  4888.0 1615.28
  4894.7 1614.86  4937.8 1614.60  4959.3 1614.07  4977.0 1611.60  4977.5 1611.10
  4984.1 1611.10  4984.6 1611.60  5001.0 1612.68  5007.0 1612.68  5017.8 1613.96
  5026.2 1614.24  5047.1 1616.32  5061.7 1616.59  5182.8 1617.25  5401.3 1617.32
#Mann=3,-1,0
  4341.6   0.035       0  4977.0   0.035       0  4984.6   0.035       0
Bank Sta=4977,4984.6
Exp/Cntr=0.3,0.1

Type RM Length L Ch R = 1,6020,341,341,341
BEGIN DESCRIPTION:
Mapping XS 1606147d
END DESCRIPTION:
XS GIS Cut Line= 3
      1634251.28      6950784.37      1634236.43      6951224.79
      1634193.29      6951468.13
#Sta/Elev= 30
  4565.0 1615.36  4648.7 1614.38  4668.7 1614.41  4698.7 1613.95  4708.7 1614.10
  4718.7 1613.76  4758.7 1613.65  4778.7 1612.11  4785.0 1611.92  4785.5 1611.42
  4792.1 1611.42  4792.6 1611.92  4828.8 1613.25  4868.8 1613.55  4901.7 1612.88
  4948.8 1613.82  4978.9 1613.25  4988.9 1612.55  4998.9 1612.28  5038.4 1612.22
  5043.5 1613.73  5049.6 1614.17  5059.7 1614.44  5110.5 1614.68  5120.6 1615.10
  5130.8 1614.92  5161.7 1615.64  5171.4 1615.42  5222.2 1615.72  5252.8 1615.36
#Mann=3,-1,0
  4565.0   0.035       0  4785.0   0.035       0  4792.6   0.035       0
Bank Sta=4785,4792.6
Exp/Cntr=0.3,0.1

Type RM Length L Ch R = 1,5679,246,246,246
BEGIN DESCRIPTION:
Mapping XS b7942bd9
END DESCRIPTION:
XS GIS Cut Line= 3
      1634204.38      6950798.32      1633906.57      6951183.13
      1633826.82      6951324.50
#Sta/Elev= 30
  4516.4 1615.09  4551.9 1614.73  4657.8 1612.42  4680.4 1612.59  4686.8 1613.00
  4693.1 1612.59  4701.3 1612.94  4786.4 1612.81  4794.2 1613.16  4807.2 1612.72
  4857.4 1612.83  4871.5 1612.30  4879.7 1612.49  4886.0 1611.89  4929.5 1611.99
  4935.8 1611.35  4958.5 1610.44  4964.8 1609.19  4975.5 1608.96  4976.0 1608.46
  4982.6 1608.46  4983.1 1608.96  4985.6 1610.25  4993.8 1611.02  5000.1 1612.76
  5015.3 1612.84  5021.1 1613.75  5052.9 1614.22  5155.5 1613.94  5165.3 1614.19
#Mann=3,-1,0
  4516.4   0.035       0  4975.5   0.035       0  4983.1   0.035       0
Bank Sta=4975.5,4983.1
Exp/Cntr=0.3,0.1

Type RM Length L Ch R = 1,5433,235,235,235
BEGIN DESCRIPTION:
Mapping XS 0328baf3
END DESCRIPTION:
XS GIS Cut Line= 3
      1634162.74      6950563.91      1633865.40      6950949.94
      1633744.32      6951221.94
#Sta/Elev= 30
  4515.2 1615.43  4581.2 1615.77  4666.3 1614.88  4672.7 1615.14  4680.9 1615.00
  4687.2 1614.46  4709.7 1614.19  4801.3 1611.23  4830.3 1611.55  4851.2 1611.24
  4901.0 1612.42  4923.7 1612.16  4944.5 1612.56  4959.0 1611.80  4973.5 1609.76
  4979.8 1609.32  5007.0 1609.06  5007.5 1608.56  5014.1 1608.56  5014.6 1609.06
  5016.3 1609.60  5022.2 1609.59  5045.0 1611.36  5068.2 1611.10  5131.7 1612.62
  5197.4 1613.16  5213.1 1613.60  5230.2 1613.29  5252.1 1613.67  5300.2 1613.56
#Mann=3,-1,0
  4515.2   0.035       0  5007.0   0.035       0  5014.6   0.035       0
Bank Sta=5007,5014.6
Exp/Cntr=0.3,0.1

Type RM Length L Ch R = 1,5198,273,273,273
BEGIN DESCRIPTION:
Mapping XS 390e3cca
END DESCRIPTION:
XS GIS Cut Line= 3
      1633627.32      6950626.08      1633690.93      6950939.53
      1633695.03      6951127.85
#Sta/Elev= 30
  4682.5 1611.92  4715.1 1611.57  4735.5 1610.93  4748.5 1610.92  4766.1 1610.44
  4799.2 1610.15  4806.9 1609.79  4837.5 1609.21  4868.1 1610.10  4900.5 1610.48
  4908.9 1610.95  4929.3 1610.51  4939.6 1609.52  4946.0 1609.28  4976.6 1608.73
  4977.1 1608.23  4983.7 1608.23  4984.2 1608.73  5000.0 1609.67  5010.8 1609.66
  5020.8 1610.00  5040.8 1609.80  5070.8 1611.10  5110.8 1611.79  5120.8 1612.27
  5130.8 1612.29  5140.8 1612.61  5170.8 1612.68  5180.8 1612.95  5190.7 1612.94
#Mann=3,-1,0
  4682.5   0.035       0  4976.6   0.035       0  4984.2   0.035       0
Bank Sta=4976.6,4984.2
Exp/Cntr=0.3,0.1

Type RM Length L Ch R = 1,4925,222,222,222
BEGIN DESCRIPTION:
Mapping XS a083b1cd
END DESCRIPTION:
XS GIS Cut Line= 3
      1633550.94      6950606.95      1633433.11      6950989.01
      1633418.99      6951290.96
#Sta/Elev= 30
  4601.2 1611.17  4638.6 1610.86  4644.2 1611.07  4671.3 1610.64  4736.6 1609.00
  4748.8 1608.43  4769.3 1608.12  4774.5 1607.61  4790.7 1608.14  4812.4 1608.18
  4839.8 1609.19  4845.1 1609.01  4853.5 1609.56  4872.5 1609.81  4937.2 1609.04
  4968.6 1608.26  4981.0 1607.52  5026.2 1607.14  5026.7 1606.64  5033.4 1606.64
  5033.9 1607.14  5040.0 1607.29  5066.4 1609.68  5071.4 1609.58  5120.1 1611.05
  5150.2 1610.98  5190.2 1611.54  5270.3 1611.53  5278.5 1611.98  5303.3 1611.44
#Mann=3,-1,0
  4601.2   0.035       0  5026.2   0.035       0  5033.9   0.035       0
Bank Sta=5026.2,5033.9
Exp/Cntr=0.3,0.1

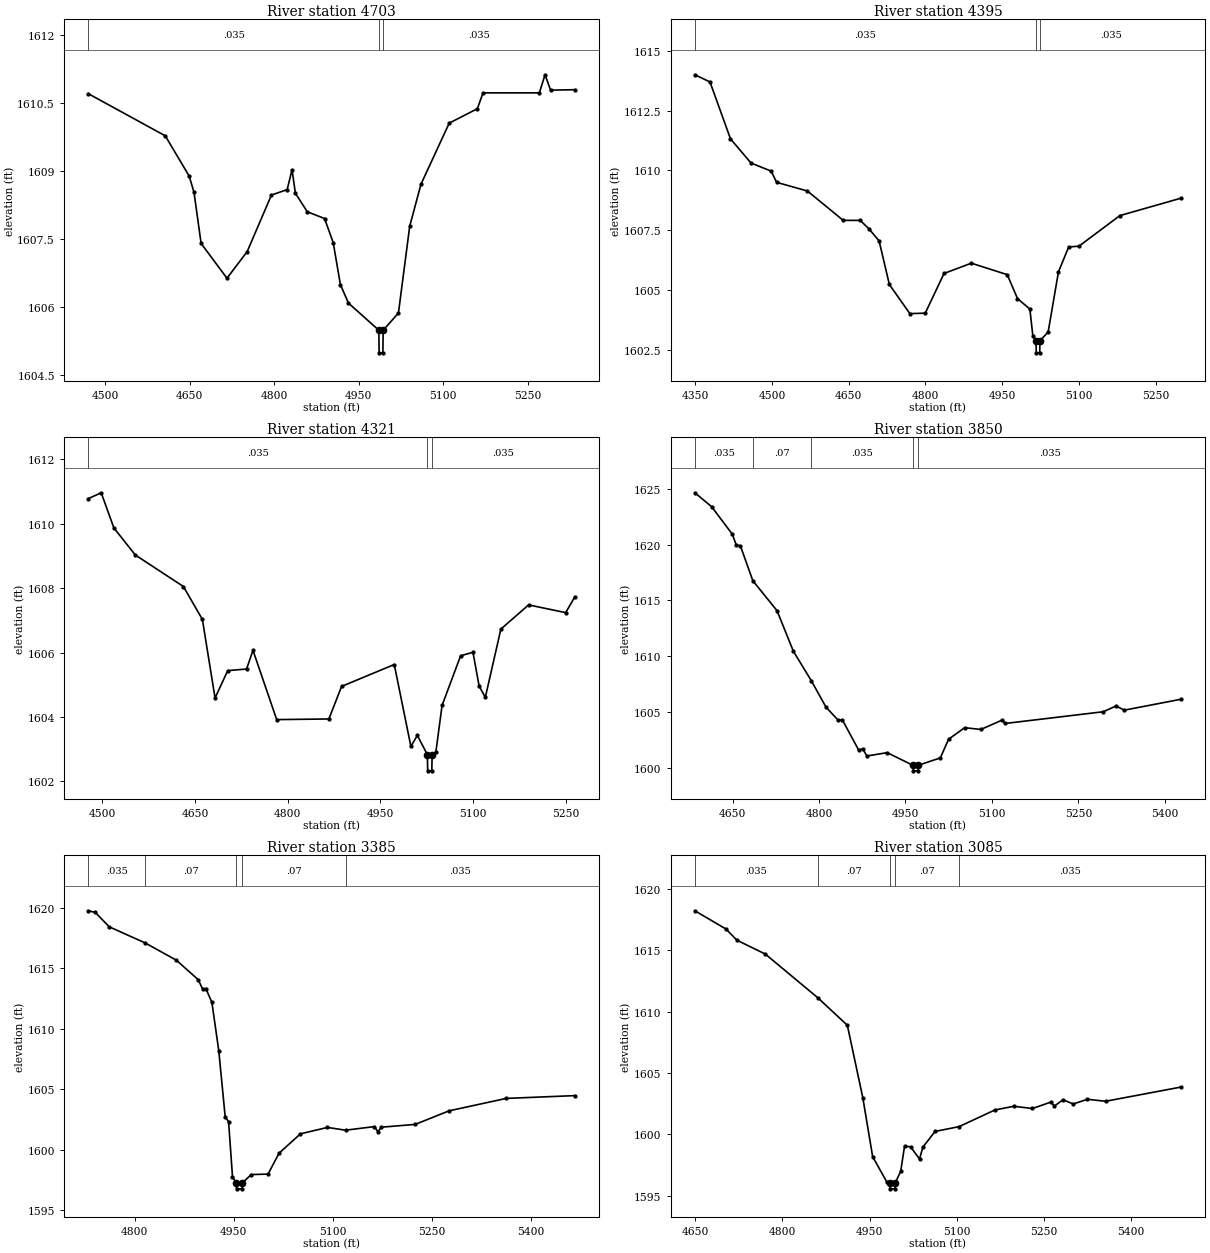
Type RM Length L Ch R = 1,4703,308,308,308
BEGIN DESCRIPTION:
Mapping XS 1d9c07de
END DESCRIPTION:
XS GIS Cut Line= 3
      1633493.62      6950539.30      1633210.46      6950990.31
      1633219.34      6951320.56
#Sta/Elev= 30
  4470.1 1610.71  4606.5 1609.78  4648.9 1608.89  4657.5 1608.53  4670.1 1607.40
  4716.0 1606.63  4751.9 1607.22  4794.9 1608.47  4822.8 1608.59  4831.5 1609.03
  4837.4 1608.51  4858.6 1608.10  4889.2 1607.95  4904.5 1607.42  4917.3 1606.49
  4931.6 1606.08  4985.5 1605.48  4986.0 1604.98  4992.7 1604.98  4993.2 1605.48
  5020.3 1605.86  5040.3 1607.78  5060.3 1608.71  5110.4 1610.06  5160.4 1610.38
  5170.4 1610.73  5270.4 1610.73  5280.4 1611.13  5290.4 1610.79  5333.0 1610.80
#Mann=3,-1,0
  4470.1   0.035       0  4985.5   0.035       0  4993.2   0.035       0
Bank Sta=4985.5,4993.2
Exp/Cntr=0.3,0.1

Type RM Length L Ch R = 1,4395,74,74,74
BEGIN DESCRIPTION:
Mapping XS 5affe1d8
END DESCRIPTION:
XS GIS Cut Line= 3
      1632959.15      6950288.53      1632920.09      6950942.13
      1632926.60      6951237.69
#Sta/Elev= 30
  4349.4 1614.00  4378.9 1613.70  4419.0 1611.32  4459.1 1610.31  4498.5 1609.97
  4509.2 1609.50  4569.3 1609.14  4639.4 1607.91  4672.5 1607.91  4689.5 1607.56
  4709.5 1607.05  4729.5 1605.23  4769.6 1604.01  4799.7 1604.03  4836.4 1605.69
  4889.8 1606.12  4960.0 1605.64  4980.0 1604.64  5004.2 1604.20  5010.0 1603.08
  5016.2 1602.87  5016.7 1602.37  5023.4 1602.37  5023.9 1602.87  5040.0 1603.25
  5060.1 1605.76  5080.1 1606.80  5100.1 1606.83  5180.1 1608.11  5299.8 1608.84
#Mann=3,-1,0
  4349.4   0.035       0  5016.2   0.035       0  5023.9   0.035       0
Bank Sta=5016.2,5023.9
Exp/Cntr=0.3,0.1

Type RM Length L Ch R = 1,4321,471,471,471
BEGIN DESCRIPTION:
Mapping XS 03b501c3
END DESCRIPTION:
XS GIS Cut Line= 3
      1632733.89      6950427.80      1632847.18      6950942.13
      1632852.38      6951202.52
#Sta/Elev= 30
  4477.6 1610.78  4498.3 1610.96  4518.8 1609.87  4553.5 1609.03  4631.4 1608.05
  4662.1 1607.03  4682.6 1604.59  4703.1 1605.44  4733.6 1605.49  4744.0 1606.07
  4782.4 1603.92  4866.9 1603.94  4887.4 1604.95  4972.7 1605.63  4999.6 1603.09
  5010.1 1603.43  5026.3 1602.83  5026.8 1602.33  5033.5 1602.33  5034.0 1602.83
  5040.1 1602.92  5050.1 1604.36  5080.1 1605.90  5100.1 1606.01  5110.1 1604.96
  5120.1 1604.61  5145.3 1606.73  5190.2 1607.48  5250.2 1607.24  5264.7 1607.72
#Mann=3,-1,0
  4477.6   0.035       0  5026.3   0.035       0  5034.0   0.035       0
Bank Sta=5026.3,5034
Exp/Cntr=0.3,0.1

Type RM Length L Ch R = 1,3850,465,465,465
BEGIN DESCRIPTION:
Mapping XS a127799b
END DESCRIPTION:
XS GIS Cut Line= 3
      1632123.23      6950728.35      1632407.54      6951035.45
      1632728.46      6951314.23
#Sta/Elev= 30
  4584.6 1624.64  4613.7 1623.39  4649.5 1620.93  4656.3 1619.97  4663.6 1619.88
  4685.2 1616.75  4727.1 1614.07  4755.5 1610.43  4786.5 1607.80  4812.2 1605.41
  4833.2 1604.25  4840.5 1604.28  4868.9 1601.56  4875.7 1601.69  4883.0 1601.04
  4918.2 1601.34  4962.8 1600.21  4963.3 1599.71  4971.7 1599.71  4972.2 1600.21
  5010.5 1600.87  5024.7 1602.54  5052.7 1603.58  5080.7 1603.42  5116.8 1604.24
  5123.5 1603.96  5293.4 1605.01  5315.3 1605.53  5329.6 1605.15  5428.2 1606.13
#Mann=5,-1,0
  4584.6   0.035       0  4685.2    0.07       0  4786.5   0.035       0
  4962.8   0.035       0  4972.2   0.035       0
Bank Sta=4962.8,4972.2
Exp/Cntr=0.3,0.1

Type RM Length L Ch R = 1,3385,300,300,300
BEGIN DESCRIPTION:
Mapping XS f023ad69
END DESCRIPTION:
XS GIS Cut Line= 3
      1631844.81      6951226.64      1632103.90      6951298.25
      1632561.10      6951394.37
#Sta/Elev= 30
  4730.0 1619.75  4740.6 1619.61  4761.3 1618.43  4815.9 1617.09  4863.2 1615.66
  4896.2 1614.05  4902.7 1613.29  4907.9 1613.30  4916.9 1612.18  4927.3 1608.18
  4937.0 1602.73  4942.2 1602.29  4948.1 1597.75  4953.7 1597.25  4954.2 1596.75
  4962.7 1596.75  4963.2 1597.25  4976.5 1597.93  5001.9 1597.97  5018.6 1599.70
  5051.0 1601.30  5091.9 1601.83  5119.2 1601.60  5163.0 1601.90  5168.1 1601.47
  5173.6 1601.85  5224.7 1602.08  5275.8 1603.20  5362.4 1604.23  5466.0 1604.46
#Mann=5,-1,0
  4730.0   0.035       0  4815.9    0.07       0  4953.7    0.07       0
  4963.2    0.07       0  5119.2   0.035       0
Bank Sta=4953.7,4963.2
Exp/Cntr=0.3,0.1

Type RM Length L Ch R = 1,3085,316,316,316
BEGIN DESCRIPTION:
Mapping XS 93e6b292
END DESCRIPTION:
XS GIS Cut Line= 3
      1631712.94      6951506.54      1632054.11      6951582.06
      1632518.94      6951727.89
#Sta/Elev= 30
  4649.3 1618.23  4702.6 1616.75  4721.7 1615.83  4770.5 1614.70  4860.5 1611.15
  4911.6 1608.90  4938.2 1603.00  4955.2 1598.18  4979.2 1596.15  4984.6 1596.06
  4985.1 1595.56  4993.6 1595.56  4994.1 1596.06  5003.4 1596.98  5010.1 1599.05
  5020.6 1598.98  5035.8 1597.99  5041.6 1598.96  5062.5 1600.24  5103.8 1600.63
  5165.5 1601.99  5197.9 1602.29  5230.2 1602.11  5261.7 1602.63  5268.0 1602.31
  5282.6 1602.82  5300.4 1602.48  5324.6 1602.86  5356.0 1602.70  5485.9 1603.86
#Mann=5,-1,0
  4649.3   0.035       0  4860.5    0.07       0  4984.6    0.07       0
  4994.1    0.07       0  5103.8   0.035       0
Bank Sta=4984.6,4994.1
Exp/Cntr=0.3,0.1

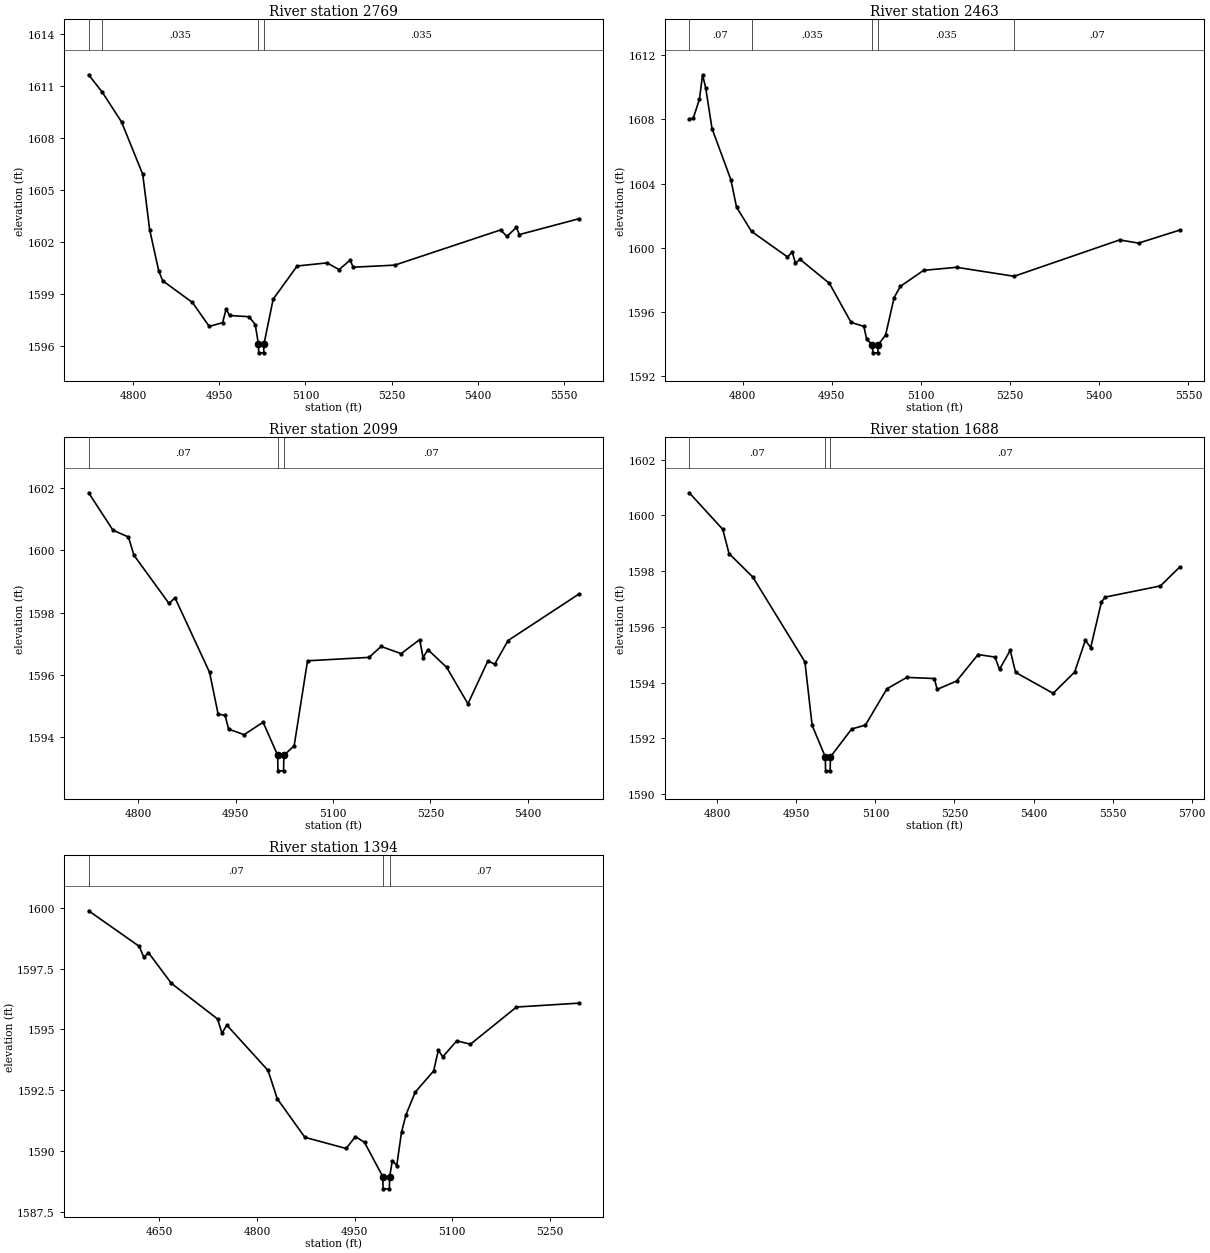
Type RM Length L Ch R = 1,2769,306,306,306
BEGIN DESCRIPTION:
Mapping XS 20122c97
END DESCRIPTION:
XS GIS Cut Line= 3
      1631763.77      6951742.23      1632004.63      6951882.84
      1632555.42      6952043.00
#Sta/Elev= 30
  4723.0 1611.63  4746.7 1610.63  4780.3 1608.91  4817.1 1605.90  4829.1 1602.72
  4844.8 1600.35  4851.8 1599.77  4903.5 1598.52  4932.8 1597.14  4956.0 1597.36
  4962.2 1598.15  4968.0 1597.77  5001.9 1597.70  5012.7 1597.25  5018.3 1596.12
  5018.8 1595.62  5027.4 1595.62  5027.9 1596.12  5043.9 1598.71  5085.6 1600.62
  5137.7 1600.80  5158.5 1600.41  5177.8 1600.96  5183.0 1600.55  5255.3 1600.67
  5439.7 1602.70  5450.1 1602.32  5466.9 1602.84  5472.1 1602.43  5575.5 1603.34
#Mann=4,-1,0
  4723.0    0.07       0  4746.7   0.035       0  5018.3   0.035       0
  5027.9   0.035       0
Bank Sta=5018.3,5027.9
Exp/Cntr=0.3,0.1

Type RM Length L Ch R = 1,2463,364,364,364
BEGIN DESCRIPTION:
Mapping XS 5b24fb35
END DESCRIPTION:
XS GIS Cut Line= 3
      1631548.79      6952025.70      1631823.35      6952120.11
      1632331.66      6952285.58
#Sta/Elev= 30
  4710.1 1608.03  4716.7 1608.07  4727.2 1609.26  4732.5 1610.79  4737.8 1609.96
  4748.4 1607.43  4780.1 1604.24  4789.7 1602.52  4814.9 1601.01  4875.3 1599.42
  4883.4 1599.72  4888.7 1599.03  4896.4 1599.27  4945.9 1597.77  4982.4 1595.33
  5003.9 1595.08  5008.6 1594.27  5018.4 1593.93  5018.9 1593.43  5027.5 1593.43
  5028.0 1593.93  5040.5 1594.55  5054.8 1596.88  5065.3 1597.58  5104.4 1598.58
  5159.9 1598.77  5256.7 1598.21  5434.2 1600.48  5466.1 1600.28  5535.0 1601.09
#Mann=5,-1,0
  4710.1    0.07       0  4814.9   0.035       0  5018.4   0.035       0
  5028.0   0.035       0  5256.7    0.07       0
Bank Sta=5018.4,5028
Exp/Cntr=0.3,0.1

Type RM Length L Ch R = 1,2099,411,411,411
BEGIN DESCRIPTION:
Mapping XS f1998e44
END DESCRIPTION:
XS GIS Cut Line= 3
      1631380.62      6952300.66      1631637.81      6952407.00
      1632100.92      6952520.84
#Sta/Elev= 30
  4723.4 1601.85  4760.9 1600.65  4784.8 1600.43  4793.1 1599.85  4847.2 1598.30
  4856.5 1598.48  4909.7 1596.09  4922.9 1594.75  4933.6 1594.71  4939.0 1594.27
  4962.9 1594.09  4992.2 1594.49  5014.6 1593.43  5015.1 1592.93  5023.7 1592.93
  5024.2 1593.43  5040.0 1593.73  5060.6 1596.46  5155.5 1596.57  5173.9 1596.92
  5204.8 1596.69  5233.4 1597.14  5238.6 1596.56  5246.0 1596.82  5274.9 1596.25
  5307.7 1595.08  5338.6 1596.46  5348.9 1596.35  5369.5 1597.11  5478.6 1598.60
#Mann=3,-1,0
  4723.4    0.07       0  5014.6    0.07       0  5024.2    0.07       0
Bank Sta=5014.6,5024.2
Exp/Cntr=0.3,0.1

Type RM Length L Ch R = 1,1688,294,294,294
BEGIN DESCRIPTION:
Mapping XS aeba5fe8
END DESCRIPTION:
XS GIS Cut Line= 3
      1631127.92      6952541.91      1631354.53      6952652.74
      1632020.55      6952778.77
#Sta/Elev= 30
  4746.9 1600.81  4810.4 1599.50  4822.4 1598.63  4867.4 1597.79  4966.3 1594.75
  4980.0 1592.47  5005.0 1591.34  5005.5 1590.84  5014.2 1590.84  5014.7 1591.34
  5055.0 1592.34  5081.1 1592.48  5121.8 1593.78  5159.7 1594.19  5212.0 1594.15
  5217.1 1593.76  5254.1 1594.06  5294.8 1595.01  5326.8 1594.92  5335.5 1594.48
  5355.8 1595.16  5366.0 1594.37  5437.3 1593.62  5478.0 1594.38  5498.3 1595.52
  5508.5 1595.26  5528.9 1596.90  5536.2 1597.07  5640.8 1597.47  5677.0 1598.14
#Mann=3,-1,0
  4746.9    0.07       0  5005.0    0.07       0  5014.7    0.07       0
Bank Sta=5005,5014.7
Exp/Cntr=0.3,0.1

Type RM Length L Ch R = 1,1394,224,224,224
BEGIN DESCRIPTION:
Mapping XS de5a5e5f
END DESCRIPTION:
XS GIS Cut Line= 3
      1631029.97      6952612.97      1631346.81      6952945.92
      1631560.09      6953148.55
#Sta/Elev= 30
  4541.1 1599.88  4618.8 1598.42  4626.1 1597.96  4633.0 1598.16  4668.5 1596.89
  4739.3 1595.43  4746.2 1594.84  4753.5 1595.18  4817.0 1593.31  4831.1 1592.15
  4873.6 1590.56  4937.1 1590.10  4951.3 1590.59  4965.4 1590.35  4993.4 1588.94
  4993.9 1588.44  5003.5 1588.44  5004.0 1588.94  5008.1 1589.60  5014.9 1589.40
  5022.2 1590.77  5029.1 1591.49  5043.3 1592.42  5071.6 1593.29  5078.8 1594.14
  5085.7 1593.87  5107.1 1594.53  5128.2 1594.39  5199.0 1595.92  5294.9 1596.08
#Mann=3,-1,0
  4541.1    0.07       0  4993.4    0.07       0  5004.0    0.07       0
Bank Sta=4993.4,5004
Exp/Cntr=0.3,0.1