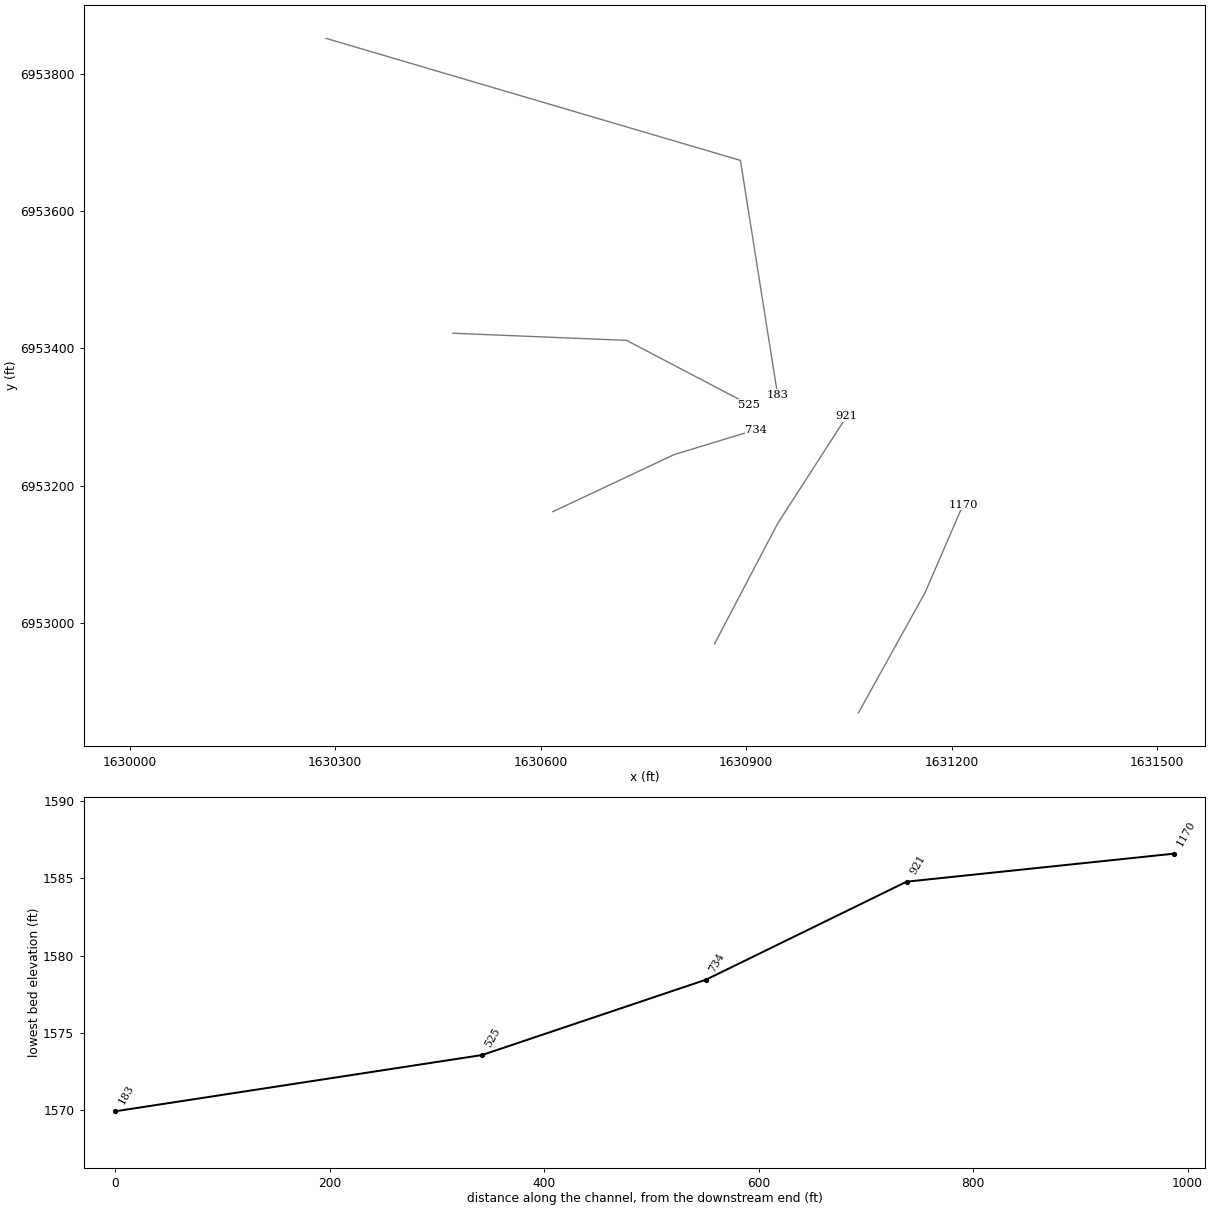
HEC-RAS study Chimney Creek 1105.prj: Chimney Creek 1105 Base Level Engineering

--- Chimney Creek 1105.g01 (geometry) --- (continued)

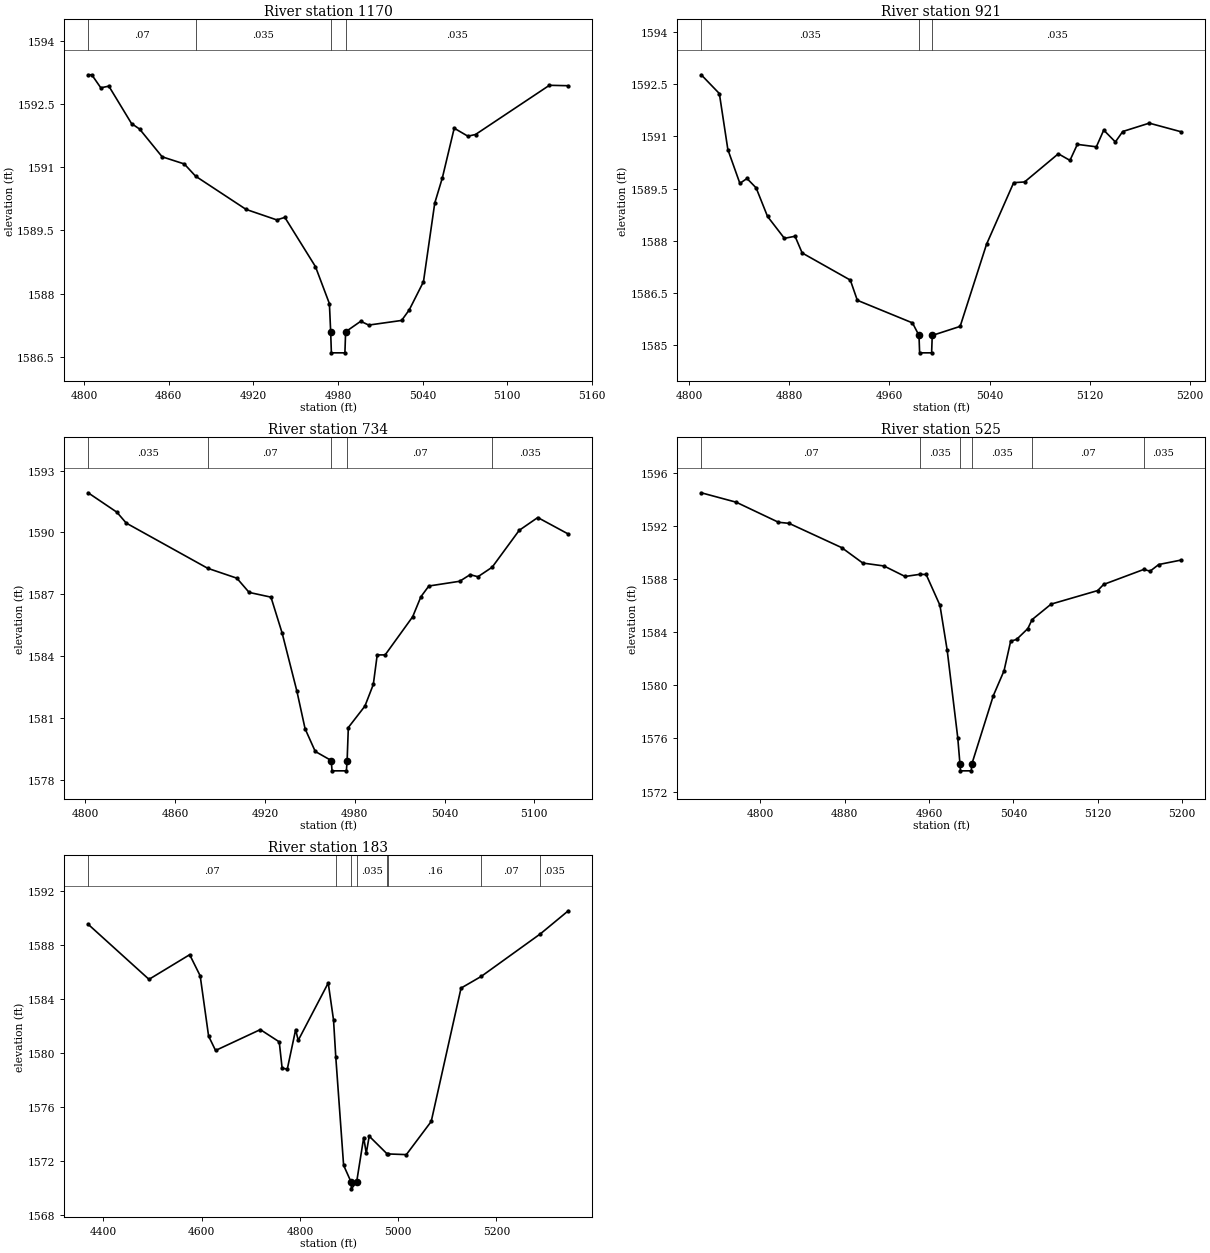
Type RM Length L Ch R = 1,1170,249,249,249
BEGIN DESCRIPTION:
Mapping XS b4fea099
END DESCRIPTION:
XS GIS Cut Line= 3
      1631063.81      6952868.39      1631161.04      6953043.75
      1631216.61      6953172.24
#Sta/Elev= 30
  4802.8 1593.20  4805.4 1593.20  4811.8 1592.89  4817.5 1592.93  4833.6 1592.04
  4839.3 1591.91  4855.3 1591.25  4871.0 1591.08  4879.0 1590.79  4914.8 1590.00
  4936.6 1589.75  4942.3 1589.81  4964.0 1588.64  4973.9 1587.76  4974.8 1587.09
  4975.3 1586.59  4984.9 1586.59  4985.4 1587.09  4996.1 1587.34  5001.8 1587.25
  5025.1 1587.36  5030.5 1587.61  5040.6 1588.28  5048.6 1590.15  5054.0 1590.75
  5062.4 1591.93  5072.1 1591.74  5077.5 1591.78  5129.9 1592.95  5143.3 1592.94
#Mann=4,-1,0
  4802.8    0.07       0  4879.0   0.035       0  4974.8   0.035       0
  4985.4   0.035       0
Bank Sta=4974.8,4985.4
Exp/Cntr=0.3,0.1

Type RM Length L Ch R = 1,921,187,187,187
BEGIN DESCRIPTION:
Mapping XS 48c16c29
END DESCRIPTION:
XS GIS Cut Line= 3
      1630853.77      6952969.13      1630945.77      6953144.45
      1631046.48      6953300.72
#Sta/Elev= 30
  4809.5 1592.77  4824.0 1592.23  4830.8 1590.62  4840.4 1589.65  4846.1 1589.79
  4853.4 1589.52  4862.5 1588.70  4876.0 1588.07  4884.5 1588.13  4890.2 1587.65
  4928.7 1586.87  4934.3 1586.29  4978.4 1585.64  4983.6 1585.28  4984.1 1584.78
  4993.7 1584.78  4994.2 1585.28  5016.5 1585.54  5037.6 1587.90  5059.3 1589.67
  5068.0 1589.69  5095.0 1590.50  5104.3 1590.31  5110.2 1590.77  5125.4 1590.70
  5131.3 1591.18  5140.6 1590.84  5146.5 1591.14  5167.7 1591.38  5193.4 1591.13
#Mann=3,-1,0
  4809.5   0.035       0  4983.6   0.035       0  4994.2   0.035       0
Bank Sta=4983.6,4994.2
Exp/Cntr=0.3,0.1

Type RM Length L Ch R = 1,734,209,209,209
BEGIN DESCRIPTION:
Mapping XS 3b810e3d
END DESCRIPTION:
XS GIS Cut Line= 3
      1630617.62      6953161.80      1630794.72      6953245.14
      1630914.47      6953281.58
#Sta/Elev= 30
  4801.8 1591.92  4821.0 1590.98  4827.3 1590.45  4881.7 1588.26  4901.2 1587.78
  4909.4 1587.09  4924.0 1586.86  4931.5 1585.11  4941.3 1582.31  4946.8 1580.48
  4953.6 1579.38  4964.3 1578.94  4964.8 1578.44  4974.4 1578.44  4974.9 1578.94
  4975.7 1580.54  4986.8 1581.58  4992.4 1582.63  4995.0 1584.06  5000.3 1584.06
  5018.7 1585.91  5024.2 1586.88  5029.5 1587.40  5050.1 1587.63  5057.1 1587.95
  5062.3 1587.85  5071.8 1588.31  5089.9 1590.10  5102.3 1590.72  5122.7 1589.92
#Mann=5,-1,0
  4801.8   0.035       0  4881.7    0.07       0  4964.3    0.07       0
  4974.9    0.07       0  5071.8   0.035       0
Bank Sta=4964.3,4974.9
Exp/Cntr=0.3,0.1

Type RM Length L Ch R = 1,525,342,342,342
BEGIN DESCRIPTION:
Mapping XS ddb6331e
END DESCRIPTION:
XS GIS Cut Line= 3
      1630471.78      6953422.22      1630725.28      6953411.81
      1630904.09      6953318.06
#Sta/Elev= 30
  4743.8 1594.49  4777.0 1593.78  4817.1 1592.27  4827.1 1592.19  4877.1 1590.36
  4897.1 1589.20  4917.2 1588.98  4937.2 1588.19  4951.1 1588.35  4957.2 1588.34
  4970.3 1586.02  4977.2 1582.62  4987.2 1576.05  4989.3 1574.06  4989.8 1573.56
  5000.0 1573.56  5000.5 1574.06  5021.0 1579.23  5031.1 1581.09  5037.4 1583.32
  5043.0 1583.45  5053.7 1584.27  5057.7 1584.94  5075.8 1586.11  5120.0 1587.13
  5125.6 1587.59  5163.7 1588.72  5169.7 1588.59  5177.9 1589.09  5199.4 1589.43
#Mann=6,-1,0
  4743.8    0.07       0  4951.1   0.035       0  4989.3   0.035       0
  5000.5   0.035       0  5057.7    0.07       0  5163.7   0.035       0
Bank Sta=4989.3,5000.5
Exp/Cntr=0.3,0.1

Type RM Length L Ch R = 1,183,0,0,0
BEGIN DESCRIPTION:
Chimney Creek 1105 1.0
END DESCRIPTION:
XS GIS Cut Line= 3
      1630286.15      6953852.67      1630891.46      6953674.46
      1630945.69      6953332.43
#Sta/Elev= 30
  4369.0 1589.56  4492.9 1585.47  4575.7 1587.30  4597.1 1585.73  4614.2 1581.26
  4628.4 1580.19  4719.5 1581.74  4758.0 1580.83  4763.9 1578.87  4774.4 1578.81
  4791.4 1581.74  4796.6 1580.94  4857.7 1585.20  4868.5 1582.45  4873.0 1579.74
  4889.0 1571.67  4904.3 1570.42  4904.8 1569.92  4915.5 1570.42  4929.9 1573.73
  4935.1 1572.56  4941.1 1573.83  4977.1 1572.53  4979.5 1572.51  5016.7 1572.46
  5067.3 1574.92  5128.0 1584.82  5169.2 1585.69  5289.6 1588.85  5346.3 1590.56
#Mann=8,-1,0
  4369.0    0.07       0  4873.0   0.035       0  4904.3    0.07       0
  4915.5   0.035       0  4977.1    0.07       0  4979.5    0.16       0
  5169.2    0.07       0  5289.6   0.035       0
Bank Sta=4904.3,4915.5
Exp/Cntr=0.3,0.1

Chan Stop Cuts=-1