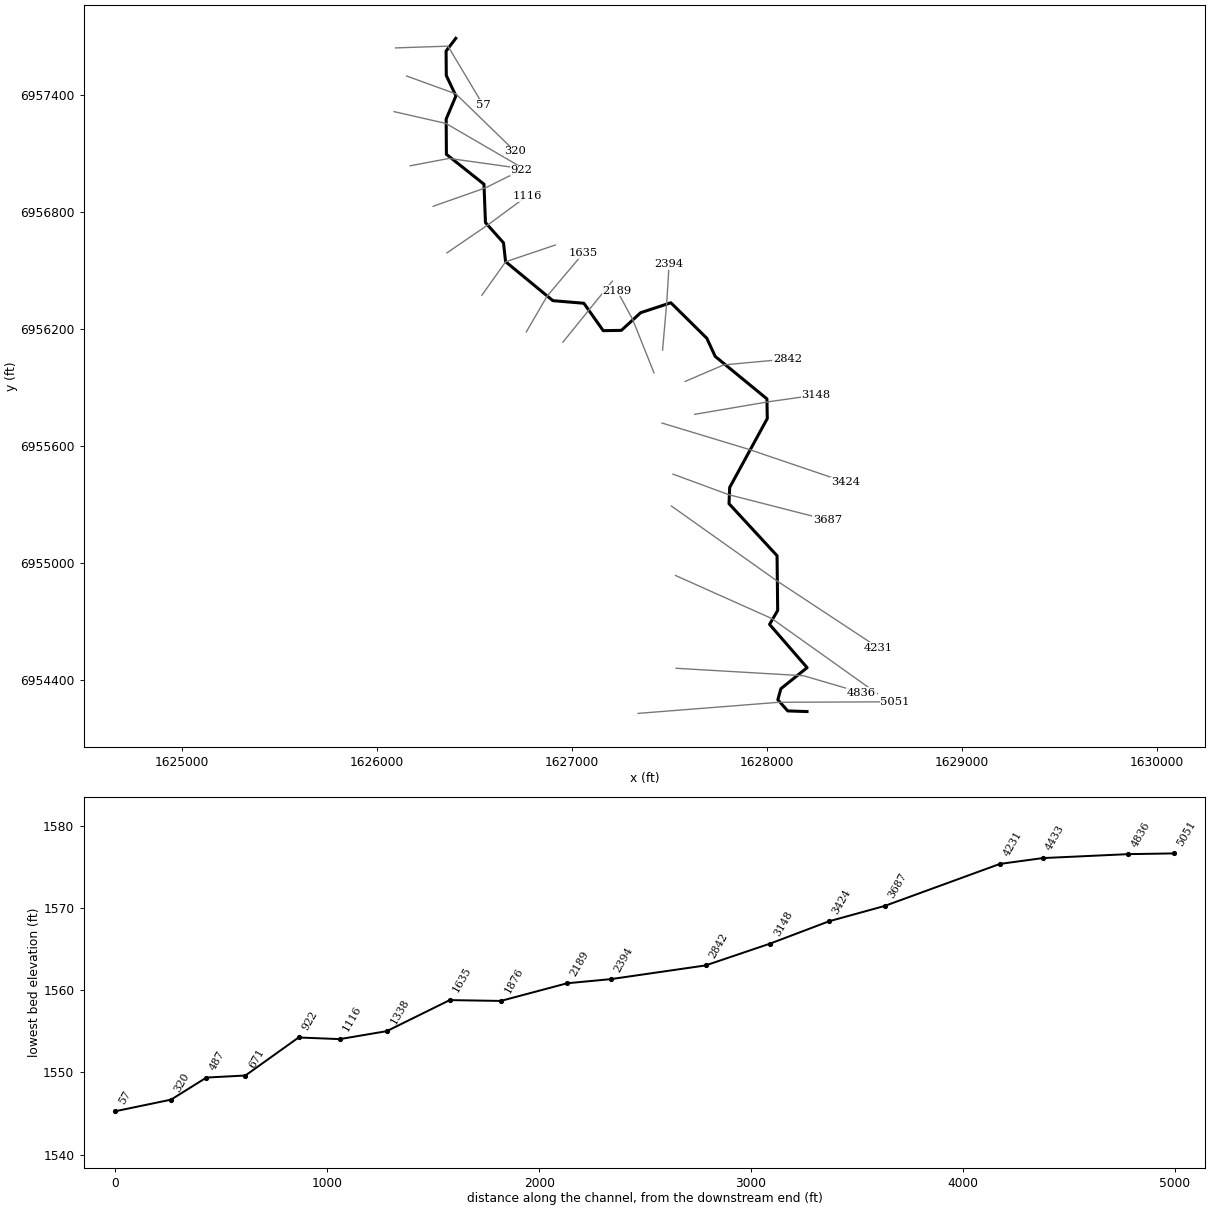
--- Chimney Creek 1106.prj (project) ---

Proj Title=Chimney Creek 1106 Base Level Engineering
Current Plan=p01
Default Exp/Contr=0.3,0.1
English Units
Geom File=g01
Flow File=f01
Plan File=p01
BEGIN DESCRIPTION:
Chimney Creek 1106
END DESCRIPTION:

--- Chimney Creek 1106.p01 (plan) ---

Plan Title=Multiple Run
Short Identifier=Multiple
Geom File=g01
Flow File=f01
Subcritical Flow
K Sum by GR= 0
Std Step Tol= 0.01
Critical Tol= 0.01
Num of Std Step Trials= 20
Max Error Tol= 0.3
Flow Tol Ratio= 0.001
Split Flow NTrial= 30
Split Flow Tol= 0.02
Split Flow Ratio= 0.02
Log Output Level= 0
Friction Slope Method= 1
Unsteady Friction Slope Method= 2
Unsteady Bridges Friction Slope Method= 1
Parabolic Critical Depth
Global Vel Dist=  1 , 1 , 1
Global Log Level= 0
CheckData=True
Encroach Param= -1, 0, 0, 0
BEGIN DESCRIPTION:
Multiple Run
END DESCRIPTION:

--- Chimney Creek 1106.f01 (steady flow) ---

Flow Title=Multiple
Number of Profiles=7
Profile Names=10-year,25-year,50-year,1pct_min,100-year,1pct_plu,500-year
River Rch & RM= Chimney Creek 11,Reach-1,5051
     177     237     284     170     339     676     487
River Rch & RM= Chimney Creek 11,Reach-1,4231
     208     281     340     205     408     815     597
Boundary for River Rch & Prof#=Chimney Creek 11,Reach-1,1
Up Type=0
Dn Type=3
Dn Slope=0.005
Boundary for River Rch & Prof#=Chimney Creek 11,Reach-1,2
Up Type=0
Dn Type=3
Dn Slope=0.005
Boundary for River Rch & Prof#=Chimney Creek 11,Reach-1,3
Up Type=0
Dn Type=3
Dn Slope=0.005
Boundary for River Rch & Prof#=Chimney Creek 11,Reach-1,4
Up Type=0
Dn Type=3
Dn Slope=0.005
Boundary for River Rch & Prof#=Chimney Creek 11,Reach-1,5
Up Type=0
Dn Type=3
Dn Slope=0.005
Boundary for River Rch & Prof#=Chimney Creek 11,Reach-1,6
Up Type=0
Dn Type=3
Dn Slope=0.005
Boundary for River Rch & Prof#=Chimney Creek 11,Reach-1,7
Up Type=0
Dn Type=3
Dn Slope=0.005

--- Chimney Creek 1106.g01 (geometry) ---

Geom Title=Existing Conditions

River Reach=Chimney Creek 11,Reach-1
Reach XY= 30
      1628205.00      6954238.00      1628106.08      6954241.28
      1628055.44      6954298.52      1628071.05      6954355.04
      1628205.48      6954462.92      1628013.03      6954684.65
      1628054.67      6954756.22      1628051.46      6955036.54
      1627805.24      6955303.22      1627808.67      6955386.41
      1628001.33      6955739.59      1627999.61      6955840.44
      1627734.61      6956057.84      1627691.37      6956151.21
      1627507.30      6956332.91      1627352.71      6956282.16
      1627253.50      6956191.47      1627160.71      6956189.89
      1627061.47      6956330.30      1626902.62      6956343.70
      1626660.26      6956543.47      1626649.44      6956640.36
      1626557.07      6956743.86      1626549.55      6956940.47
      1626356.98      6957093.67      1626355.68      6957274.08
      1626405.81      6957393.03      1626356.37      6957497.66
      1626355.34      6957622.84      1626405.00      6957688.00

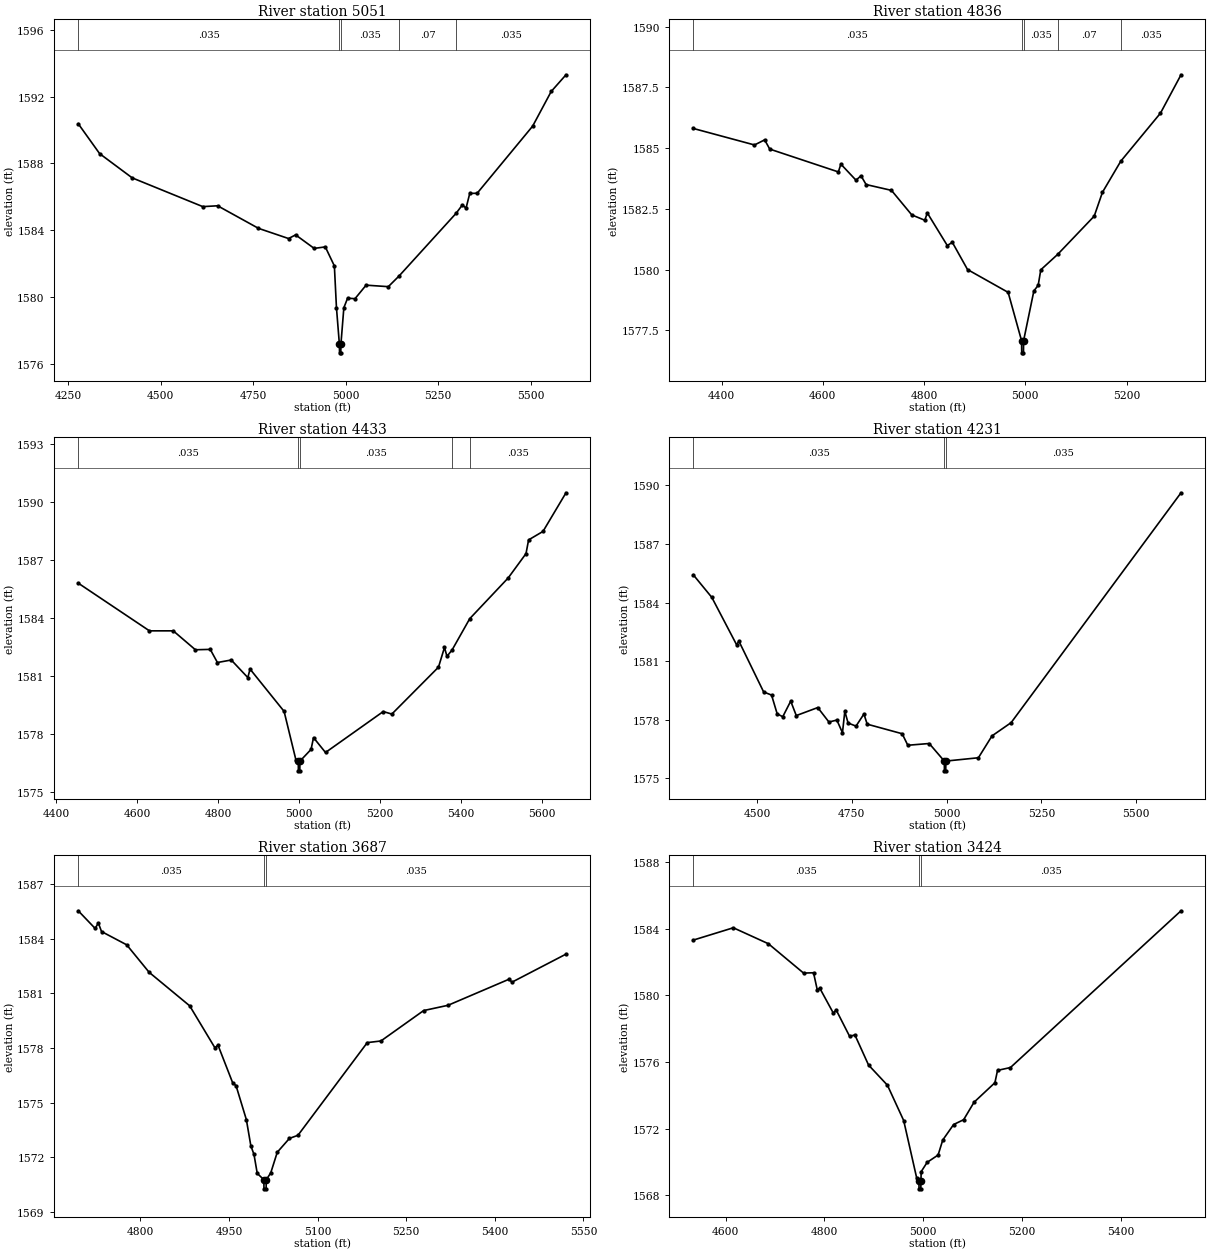
Type RM Length L Ch R = 1,5051,215,215,215
BEGIN DESCRIPTION:
Chimney Creek 1106 6.0
END DESCRIPTION:
XS GIS Cut Line= 3
      1627339.64      6954228.67      1628059.91      6954285.46
      1628655.00      6954288.00
#Sta/Elev= 30
  4277.5 1590.37  4335.3 1588.58  4423.3 1587.13  4613.9 1585.41  4654.0 1585.46
  4764.4 1584.11  4845.6 1583.50  4864.7 1583.72  4914.8 1582.91  4944.9 1583.00
  4969.4 1581.86  4975.0 1579.37  4983.0 1577.16  4983.3 1576.66  4986.8 1576.66
  4987.0 1577.16  4995.0 1579.36  5005.1 1579.93  5025.1 1579.90  5055.1 1580.71
  5115.1 1580.62  5144.2 1581.26  5298.2 1585.01  5315.1 1585.51  5325.1 1585.32
  5335.1 1586.20  5355.1 1586.21  5505.1 1590.23  5555.1 1592.30  5595.1 1593.30
#Mann=5,-1,0
  4277.5   0.035       0  4983.0   0.035       0  4987.0   0.035       0
  5144.2    0.07       0  5298.2   0.035       0
Bank Sta=4983,4987
Exp/Cntr=0.3,0.1

Type RM Length L Ch R = 1,4836,403,403,403
BEGIN DESCRIPTION:
Mapping XS f7e286c4
END DESCRIPTION:
XS GIS Cut Line= 3
      1627534.28      6954459.75      1628187.03      6954421.55
      1628483.93      6954334.74
#Sta/Elev= 30
  4344.2 1585.81  4465.1 1585.13  4485.2 1585.34  4495.2 1584.96  4630.7 1584.02
  4635.7 1584.34  4665.5 1583.68  4675.5 1583.86  4685.5 1583.50  4735.6 1583.26
  4775.7 1582.25  4801.4 1582.03  4806.4 1582.33  4845.8 1580.99  4855.8 1581.12
  4885.8 1580.00  4966.0 1579.06  4992.5 1577.07  4992.8 1576.57  4996.3 1576.57
  4996.5 1577.07  5016.8 1579.12  5025.3 1579.35  5030.5 1579.99  5063.6 1580.62
  5136.0 1582.20  5152.2 1583.18  5188.4 1584.46  5266.8 1586.44  5307.4 1588.02
#Mann=5,-1,0
  4344.2   0.035       0  4992.5   0.035       0  4996.5   0.035       0
  5063.6    0.07       0  5188.4   0.035       0
Bank Sta=4992.5,4996.5
Exp/Cntr=0.3,0.1

Type RM Length L Ch R = 1,4433,202,202,202
BEGIN DESCRIPTION:
Mapping XS 471f6ac9
END DESCRIPTION:
XS GIS Cut Line= 3
      1627530.77      6954935.45      1628023.83      6954714.96
      1628565.49      6954329.55
#Sta/Elev= 30
  4454.2 1585.81  4630.1 1583.34  4688.9 1583.34  4743.6 1582.36  4780.3 1582.38
  4798.0 1581.70  4832.2 1581.83  4873.1 1580.92  4878.6 1581.36  4962.7 1579.17
  4992.2 1576.63  4997.8 1576.59  4998.0 1576.09  5001.5 1576.09  5001.8 1576.59
  5029.3 1577.20  5035.4 1577.81  5065.0 1577.04  5207.6 1579.16  5228.9 1579.03
  5344.1 1581.46  5358.9 1582.48  5365.0 1582.02  5377.7 1582.35  5421.3 1583.97
  5516.3 1586.08  5560.3 1587.34  5566.7 1588.05  5602.3 1588.49  5659.1 1590.49
#Mann=5,-1,0
  4454.2   0.035       0  4997.8   0.035       0  5001.8   0.035       0
  5377.7    0.07       0  5421.3   0.035       0
Bank Sta=4997.8,5001.8
Exp/Cntr=0.3,0.1

Type RM Length L Ch R = 1,4231,544,544,544
BEGIN DESCRIPTION:
Mapping XS 2c261e0a
END DESCRIPTION:
XS GIS Cut Line= 3
      1627509.96      6955291.33      1628053.35      6954905.93
      1628571.26      6954564.70
#Sta/Elev= 30
  4331.8 1585.42  4380.8 1584.26  4446.0 1581.84  4452.2 1582.02  4517.4 1579.42
  4538.3 1579.26  4553.1 1578.30  4567.8 1578.15  4588.8 1578.95  4603.5 1578.21
  4660.1 1578.62  4689.6 1577.88  4710.5 1577.98  4725.3 1577.33  4731.5 1578.43
  4740.1 1577.83  4761.0 1577.67  4781.9 1578.29  4790.5 1577.77  4882.8 1577.28
  4897.6 1576.69  4954.1 1576.78  4993.9 1575.88  4994.2 1575.38  4997.7 1575.38
  4997.9 1575.88  5083.8 1576.05  5119.7 1577.17  5170.2 1577.85  5618.2 1589.62
#Mann=3,-1,0
  4331.8   0.035       0  4993.9   0.035       0  4997.9   0.035       0
Bank Sta=4993.9,4997.9
Exp/Cntr=0.3,0.1

Type RM Length L Ch R = 1,3687,263,263,263
BEGIN DESCRIPTION:
Mapping XS 5b98cd75
END DESCRIPTION:
XS GIS Cut Line= 3
      1627518.01      6955454.69      1627804.47      6955349.22
      1628308.38      6955220.31
#Sta/Elev= 30
  4695.0 1585.53  4723.6 1584.56  4729.0 1584.86  4734.4 1584.39  4777.0 1583.66
  4815.0 1582.15  4883.6 1580.31  4926.2 1578.01  4931.5 1578.15  4956.6 1576.06
  4962.0 1575.93  4979.5 1574.06  4987.1 1572.62  4992.4 1572.15  4997.9 1571.11
  5009.1 1570.76  5009.3 1570.26  5012.9 1570.26  5013.2 1570.76  5020.8 1571.14
  5031.8 1572.27  5052.4 1573.03  5066.8 1573.20  5184.1 1578.29  5207.2 1578.38
  5279.5 1580.05  5320.8 1580.34  5423.9 1581.77  5429.0 1581.61  5520.4 1583.15
#Mann=3,-1,0
  4695.0   0.035       0  5009.1   0.035       0  5013.2   0.035       0
Bank Sta=5009.1,5013.2
Exp/Cntr=0.3,0.1

Type RM Length L Ch R = 1,3424,276,276,276
BEGIN DESCRIPTION:
Mapping XS 85dc4ee8
END DESCRIPTION:
XS GIS Cut Line= 3
      1627461.98      6955716.42      1627904.73      6955582.29
      1628401.76      6955413.59
#Sta/Elev= 30
  4534.4 1583.32  4615.5 1584.06  4686.6 1583.10  4757.7 1581.34  4777.9 1581.36
  4785.4 1580.34  4790.6 1580.43  4818.3 1578.92  4823.5 1579.14  4851.0 1577.54
  4861.6 1577.63  4889.3 1575.82  4927.5 1574.61  4960.4 1572.49  4986.9 1569.02
  4991.3 1568.89  4991.5 1568.39  4995.1 1568.39  4995.4 1568.89  4995.8 1569.42
  5007.9 1569.98  5030.1 1570.42  5039.5 1571.32  5061.5 1572.25  5081.8 1572.54
  5102.9 1573.59  5145.1 1574.76  5150.4 1575.50  5176.5 1575.67  5521.9 1585.08
#Mann=3,-1,0
  4534.4   0.035       0  4991.3   0.035       0  4995.4   0.035       0
Bank Sta=4991.3,4995.4
Exp/Cntr=0.3,0.1

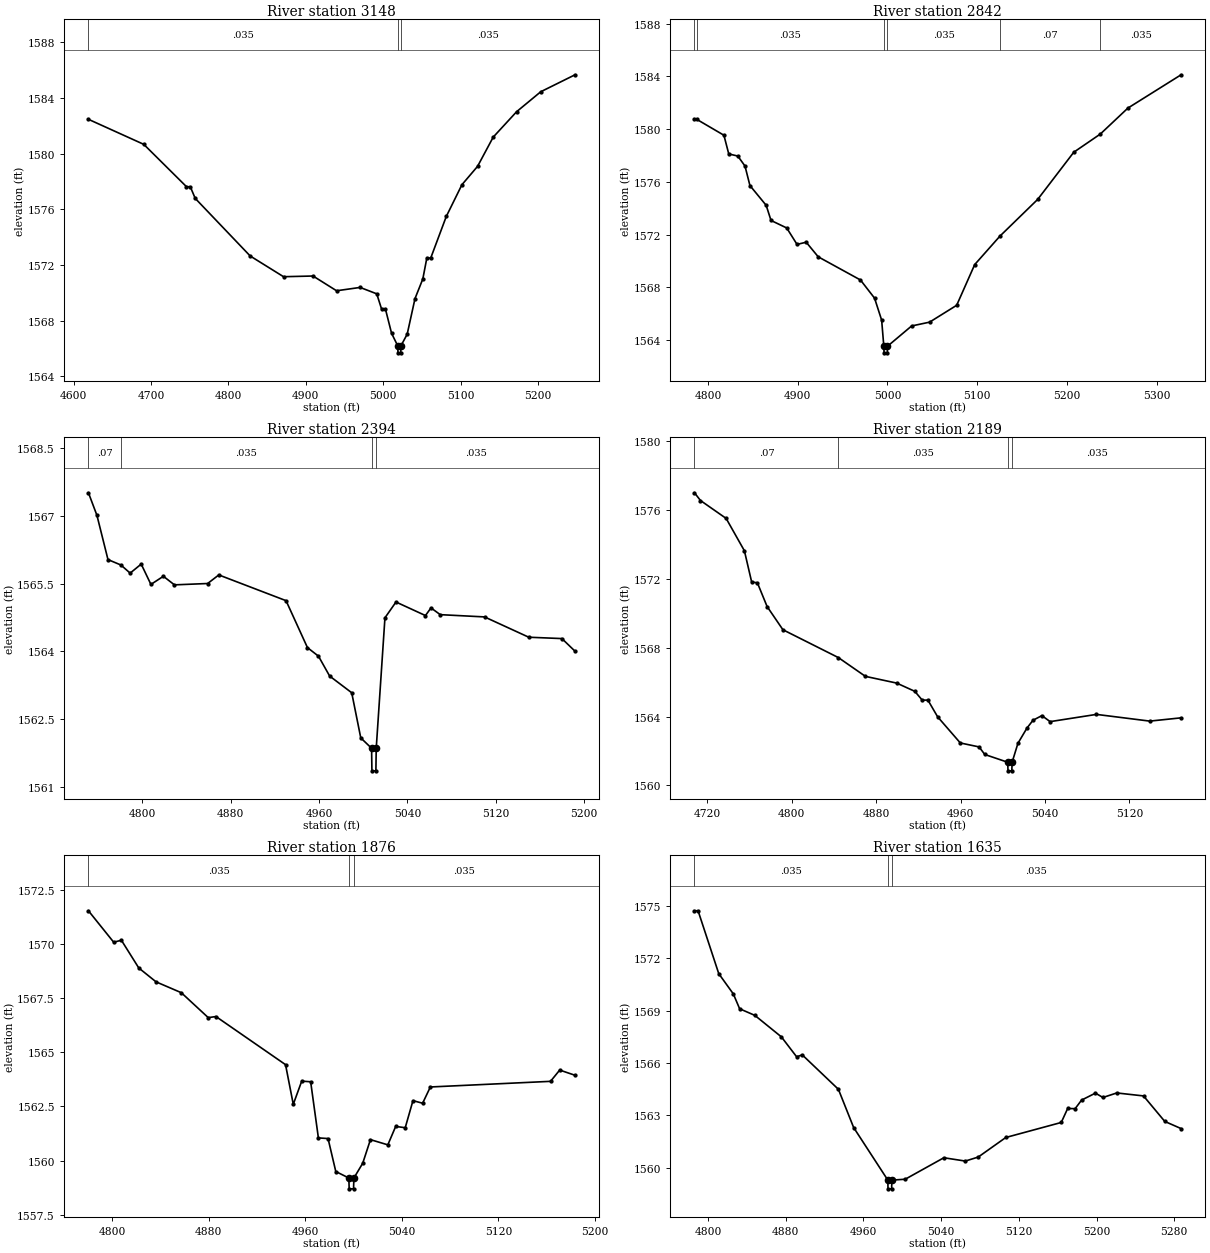
Type RM Length L Ch R = 1,3148,306,306,306
BEGIN DESCRIPTION:
Mapping XS 5a2d8408
END DESCRIPTION:
XS GIS Cut Line= 3
      1627629.04      6955761.07      1628004.49      6955825.09
      1628249.68      6955859.81
#Sta/Elev= 30
  4619.2 1582.47  4690.7 1580.67  4745.8 1577.63  4750.8 1577.62  4757.1 1576.79
  4828.1 1572.65  4871.2 1571.16  4909.3 1571.21  4939.7 1570.15  4970.1 1570.39
  4991.6 1569.93  4997.8 1568.84  5002.8 1568.84  5010.7 1567.10  5018.7 1566.19
  5019.0 1565.69  5022.6 1565.69  5022.8 1566.19  5030.9 1567.03  5041.0 1569.59
  5051.1 1571.00  5056.3 1572.51  5061.3 1572.50  5081.4 1575.49  5101.6 1577.77
  5121.8 1579.09  5142.0 1581.19  5172.3 1583.02  5203.4 1584.45  5247.7 1585.67
#Mann=3,-1,0
  4619.2   0.035       0  5018.7   0.035       0  5022.8   0.035       0
Bank Sta=5018.7,5022.8
Exp/Cntr=0.3,0.1

Type RM Length L Ch R = 1,2842,448,448,448
BEGIN DESCRIPTION:
Mapping XS 1fb894ec
END DESCRIPTION:
XS GIS Cut Line= 3
      1627580.57      6955929.80      1627778.25      6956014.59
      1628104.08      6956044.53
#Sta/Elev= 30
  4784.9 1580.74  4787.6 1580.74  4817.7 1579.54  4823.1 1578.12  4833.2 1577.96
  4841.2 1577.20  4846.7 1575.72  4864.8 1574.22  4870.2 1573.07  4887.7 1572.50
  4899.2 1571.25  4909.4 1571.42  4922.8 1570.31  4969.9 1568.55  4985.6 1567.17
  4993.5 1565.50  4995.9 1563.52  4996.2 1563.02  4999.8 1563.02  5000.0 1563.52
  5026.9 1565.06  5046.9 1565.35  5077.1 1566.63  5097.2 1569.72  5125.3 1571.88
  5167.4 1574.67  5207.6 1578.25  5237.2 1579.63  5267.9 1581.60  5327.2 1584.13
#Mann=6,-1,0
  4784.9    0.07       0  4787.6   0.035       0  4995.9   0.035       0
  5000.0   0.035       0  5125.3    0.07       0  5237.2   0.035       0
Bank Sta=4995.9,5000
Exp/Cntr=0.3,0.1

Type RM Length L Ch R = 1,2394,205,205,205
BEGIN DESCRIPTION:
Mapping XS 30df8279
END DESCRIPTION:
XS GIS Cut Line= 3
      1627464.71      6956090.37      1627486.58      6956339.28
      1627498.04      6956529.87
#Sta/Elev= 30
  4751.1 1567.51  4758.8 1567.01  4768.8 1566.03  4780.5 1565.91  4788.9 1565.73
  4798.9 1565.93  4807.7 1565.48  4819.0 1565.66  4829.0 1565.47  4859.1 1565.50
  4869.2 1565.69  4930.1 1565.12  4949.5 1564.08  4959.5 1563.89  4969.6 1563.45
  4989.6 1563.08  4997.8 1562.08  5007.6 1561.85  5007.9 1561.35  5011.5 1561.35
  5011.8 1561.85  5019.7 1564.74  5029.7 1565.09  5056.4 1564.79  5061.4 1564.96
  5069.8 1564.81  5109.9 1564.76  5150.0 1564.31  5180.0 1564.28  5191.9 1564.00
#Mann=4,-1,0
  4751.1    0.07       0  4780.5   0.035       0  5007.6   0.035       0
  5011.8   0.035       0
Bank Sta=5007.6,5011.8
Exp/Cntr=0.3,0.1

Type RM Length L Ch R = 1,2189,313,313,313
BEGIN DESCRIPTION:
Mapping XS 13d41755
END DESCRIPTION:
XS GIS Cut Line= 3
      1627420.67      6955974.08      1627312.27      6956245.43
      1627232.27      6956394.18
#Sta/Elev= 30
  4707.8 1577.01  4713.5 1576.56  4737.8 1575.52  4755.1 1573.64  4762.0 1571.82
  4767.4 1571.78  4776.6 1570.40  4791.6 1569.05  4844.2 1567.43  4869.8 1566.34
  4899.4 1565.95  4916.6 1565.47  4923.6 1564.96  4929.0 1564.96  4938.2 1563.99
  4959.7 1562.47  4977.5 1562.24  4982.9 1561.80  5004.6 1561.35  5004.9 1560.85
  5008.5 1560.85  5008.8 1561.35  5014.3 1562.45  5022.9 1563.34  5028.6 1563.79
  5037.0 1564.06  5044.8 1563.71  5088.7 1564.13  5139.2 1563.74  5168.9 1563.93
#Mann=4,-1,0
  4707.8    0.07       0  4844.2   0.035       0  5004.6   0.035       0
  5008.8   0.035       0
Bank Sta=5004.6,5008.8
Exp/Cntr=0.3,0.1

Type RM Length L Ch R = 1,1876,241,241,241
BEGIN DESCRIPTION:
Mapping XS 5fd0b1b9
END DESCRIPTION:
XS GIS Cut Line= 3
      1626953.78      6956130.64      1627091.25      6956300.75
      1627207.32      6956443.76
#Sta/Elev= 30
  4780.5 1571.53  4801.4 1570.08  4807.8 1570.17  4822.2 1568.89  4836.5 1568.25
  4857.4 1567.75  4879.7 1566.60  4886.1 1566.65  4943.7 1564.43  4950.1 1562.60
  4957.1 1563.67  4964.5 1563.64  4970.9 1561.05  4978.9 1561.02  4985.3 1559.50
  4996.1 1559.20  4996.4 1558.70  5000.0 1558.70  5000.3 1559.20  5007.6 1559.88
  5014.0 1560.97  5028.4 1560.73  5034.9 1561.58  5042.8 1561.52  5049.2 1562.77
  5057.2 1562.65  5063.6 1563.40  5163.1 1563.66  5170.7 1564.18  5183.4 1563.94
#Mann=3,-1,0
  4780.5   0.035       0  4996.1   0.035       0  5000.3   0.035       0
Bank Sta=4996.1,5000.3
Exp/Cntr=0.3,0.1

Type RM Length L Ch R = 1,1635,297,297,297
BEGIN DESCRIPTION:
Mapping XS b20a3cfb
END DESCRIPTION:
XS GIS Cut Line= 3
      1626766.26      6956183.40      1626873.89      6956368.11
      1627059.33      6956587.58
#Sta/Elev= 30
  4786.0 1574.72  4789.7 1574.72  4811.0 1571.12  4826.0 1569.96  4832.5 1569.11
  4848.2 1568.73  4875.5 1567.50  4891.2 1566.36  4897.0 1566.47  4934.2 1564.50
  4949.9 1562.31  4985.1 1559.30  4985.3 1558.80  4989.0 1558.80  4989.3 1559.30
  5003.0 1559.35  5042.8 1560.58  5064.9 1560.39  5078.2 1560.62  5106.6 1561.74
  5163.7 1562.60  5170.3 1563.40  5178.0 1563.39  5184.6 1563.88  5198.9 1564.28
  5206.6 1564.03  5220.9 1564.29  5248.4 1564.12  5270.3 1562.66  5287.1 1562.25
#Mann=3,-1,0
  4786.0   0.035       0  4985.1   0.035       0  4989.3   0.035       0
Bank Sta=4985.1,4989.3
Exp/Cntr=0.3,0.1

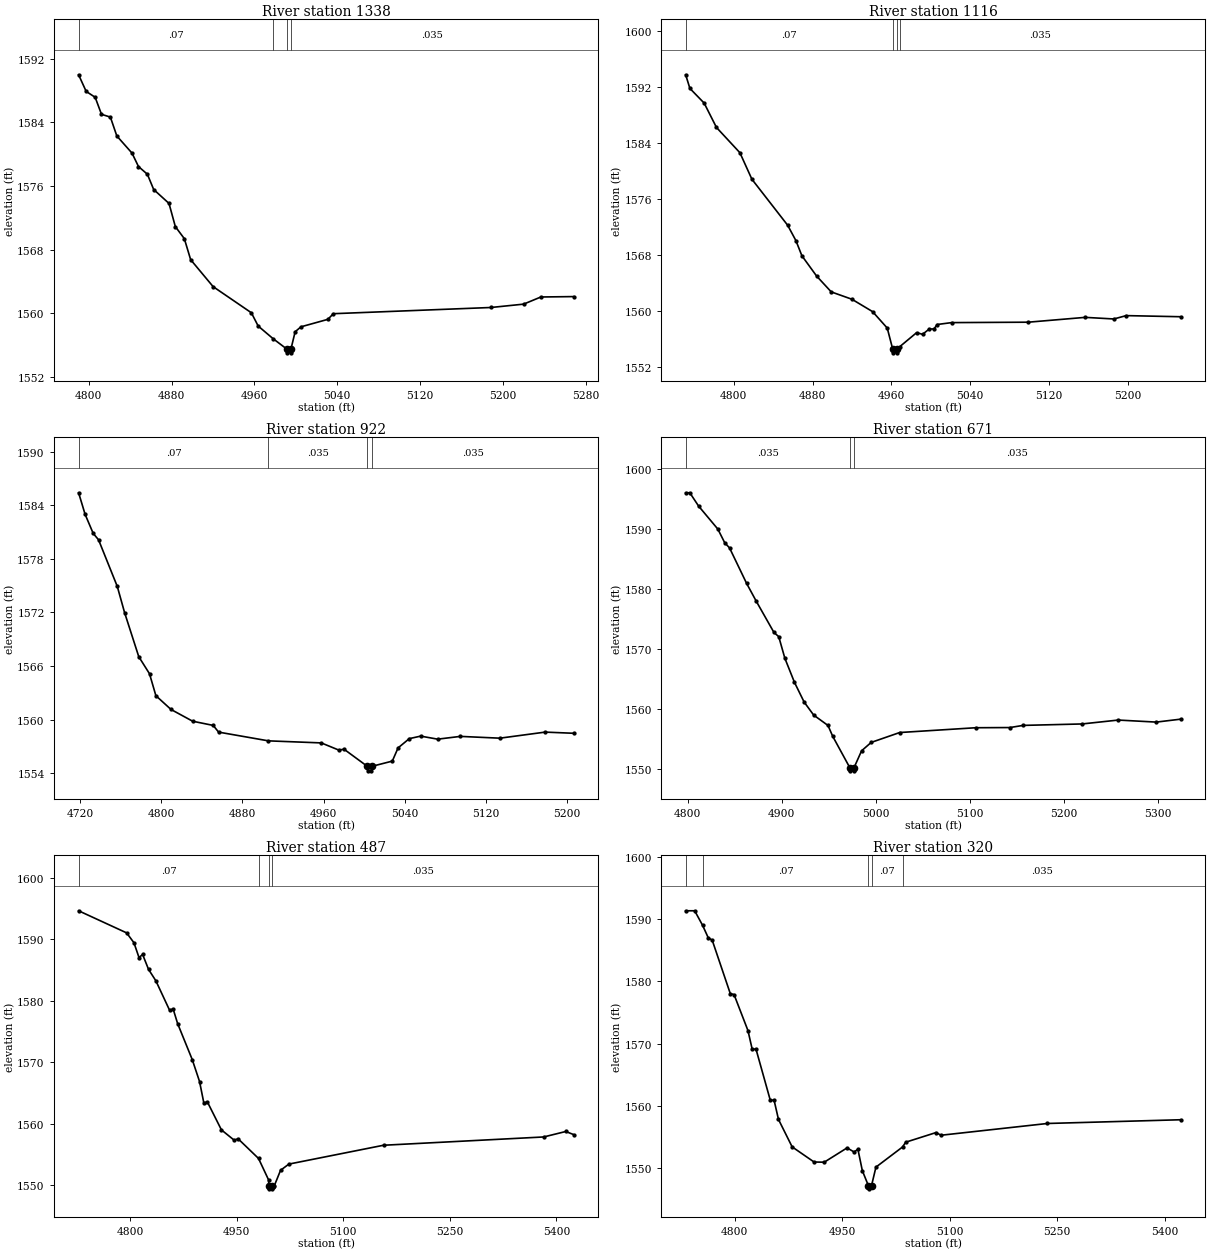
Type RM Length L Ch R = 1,1338,222,222,222
BEGIN DESCRIPTION:
Mapping XS 87fc3ef7
END DESCRIPTION:
XS GIS Cut Line= 3
      1626539.27      6956372.07      1626660.81      6956543.10
      1626914.99      6956628.66
#Sta/Elev= 30
  4790.2 1589.97  4797.5 1587.88  4806.2 1587.14  4812.3 1585.00  4820.9 1584.65
  4827.1 1582.28  4841.8 1580.12  4848.0 1578.44  4856.6 1577.47  4862.7 1575.55
  4877.5 1573.80  4883.6 1570.89  4892.3 1569.37  4898.4 1566.73  4920.1 1563.34
  4957.0 1560.06  4963.6 1558.39  4978.0 1556.80  4991.0 1555.52  4991.3 1555.02
  4995.0 1555.02  4995.3 1555.52  4999.3 1557.67  5004.9 1558.29  5030.9 1559.23
  5036.2 1559.94  5188.4 1560.72  5219.9 1561.14  5236.6 1562.04  5268.2 1562.09
#Mann=4,-1,0
  4790.2    0.07       0  4978.0   0.035       0  4991.0   0.035       0
  4995.3   0.035       0
Bank Sta=4991,4995.3
Exp/Cntr=0.3,0.1

Type RM Length L Ch R = 1,1116,194,194,194
BEGIN DESCRIPTION:
Mapping XS fbf60598
END DESCRIPTION:
XS GIS Cut Line= 3
      1626359.45      6956588.53      1626567.82      6956730.71
      1626769.63      6956879.35
#Sta/Elev= 30
  4751.1 1593.79  4755.4 1591.84  4769.9 1589.74  4782.4 1586.26  4806.2 1582.65
  4818.4 1578.86  4854.7 1572.29  4863.1 1570.09  4869.2 1567.92  4884.1 1565.03
  4899.0 1562.76  4920.0 1561.71  4941.0 1559.94  4955.9 1557.59  4961.5 1554.55
  4961.8 1554.05  4965.5 1554.05  4965.8 1554.55  4968.6 1554.93  4985.7 1556.93
  4991.8 1556.70  4998.6 1557.46  5003.4 1557.46  5006.6 1558.10  5021.3 1558.37
  5099.2 1558.43  5157.0 1559.12  5186.1 1558.89  5198.7 1559.37  5254.0 1559.21
#Mann=4,-1,0
  4751.1    0.07       0  4961.5   0.035       0  4965.8    0.07       0
  4968.6   0.035       0
Bank Sta=4961.5,4965.8
Exp/Cntr=0.3,0.1

Type RM Length L Ch R = 1,922,251,251,251
BEGIN DESCRIPTION:
Mapping XS af4395c5
END DESCRIPTION:
XS GIS Cut Line= 3
      1626289.00      6956827.29      1626556.97      6956921.68
      1626740.18      6957012.74
#Sta/Elev= 30
  4718.2 1585.41  4724.6 1583.00  4732.6 1580.86  4737.9 1580.14  4756.4 1574.91
  4763.6 1571.98  4777.6 1567.04  4788.2 1565.13  4794.5 1562.67  4809.4 1561.13
  4830.8 1559.81  4851.1 1559.34  4856.4 1558.59  4905.6 1557.61  4957.8 1557.38
  4975.0 1556.58  4980.3 1556.67  5003.3 1554.75  5003.6 1554.25  5007.3 1554.25
  5007.6 1554.75  5027.9 1555.34  5033.6 1556.82  5044.7 1557.86  5055.9 1558.14
  5072.7 1557.80  5095.1 1558.11  5134.1 1557.91  5178.8 1558.59  5206.9 1558.46
#Mann=4,-1,0
  4718.2    0.07       0  4905.6   0.035       0  5003.3   0.035       0
  5007.6   0.035       0
Bank Sta=5003.3,5007.6
Exp/Cntr=0.3,0.1

Type RM Length L Ch R = 1,671,184,184,184
BEGIN DESCRIPTION:
Mapping XS 4eae76d9
END DESCRIPTION:
XS GIS Cut Line= 3
      1626171.40      6957034.85      1626370.62      6957072.61
      1626690.67      6957028.13
#Sta/Elev= 30
  4798.0 1596.00  4802.4 1596.00  4811.8 1593.77  4832.2 1589.94  4839.5 1587.66
  4844.6 1586.81  4862.7 1580.90  4872.9 1577.94  4891.8 1572.70  4896.9 1572.00
  4903.4 1568.39  4913.6 1564.38  4923.8 1561.11  4934.0 1558.92  4949.2 1557.19
  4954.3 1555.36  4972.5 1550.12  4972.8 1549.62  4976.5 1549.62  4976.8 1550.12
  4984.9 1552.96  4995.1 1554.36  5025.4 1556.01  5106.2 1556.81  5142.4 1556.84
  5156.6 1557.20  5219.1 1557.44  5257.6 1558.09  5298.0 1557.75  5323.9 1558.24
#Mann=3,-1,0
  4798.0   0.035       0  4972.5   0.035       0  4976.8   0.035       0
Bank Sta=4972.5,4976.8
Exp/Cntr=0.3,0.1

Type RM Length L Ch R = 1,487,167,167,167
BEGIN DESCRIPTION:
Mapping XS 00861cb0
END DESCRIPTION:
XS GIS Cut Line= 3
      1626089.07      6957312.34      1626354.56      6957251.82
      1626721.40      6957038.61
#Sta/Elev= 30
  4727.7 1594.66  4795.3 1591.06  4805.6 1589.45  4812.7 1587.04  4817.8 1587.54
  4826.1 1585.12  4836.4 1583.26  4855.7 1578.47  4860.8 1578.64  4867.1 1576.27
  4887.6 1570.43  4897.9 1566.85  4903.9 1563.38  4909.0 1563.51  4928.7 1558.97
  4946.9 1557.27  4952.0 1557.54  4980.9 1554.32  4995.0 1550.84  4995.5 1549.87
  4995.8 1549.37  4999.5 1549.37  4999.8 1549.87  5003.1 1549.87  5011.9 1552.39
  5023.6 1553.40  5156.8 1556.47  5382.2 1557.82  5413.3 1558.71  5424.3 1558.21
#Mann=4,-1,0
  4727.7    0.07       0  4980.9   0.035       0  4995.5   0.035       0
  4999.8   0.035       0
Bank Sta=4995.5,4999.8
Exp/Cntr=0.3,0.1

Type RM Length L Ch R = 1,320,263,263,263
BEGIN DESCRIPTION:
Mapping XS 23d7b08e
END DESCRIPTION:
XS GIS Cut Line= 3
      1626153.20      6957494.91      1626405.71      6957403.06
      1626708.64      6957108.55
#Sta/Elev= 30
  4731.3 1591.35  4743.9 1591.35  4754.9 1589.02  4763.0 1586.97  4768.3 1586.65
  4793.6 1578.05  4798.9 1577.88  4818.3 1572.10  4824.2 1569.11  4829.5 1569.13
  4849.4 1560.94  4854.8 1560.90  4860.9 1557.83  4880.0 1553.42  4910.6 1550.99
  4924.8 1550.96  4956.7 1553.26  4966.5 1552.60  4971.8 1553.04  4978.0 1549.60
  4986.5 1547.18  4986.8 1546.68  4990.8 1547.18  4997.0 1550.17  5034.1 1553.40
  5038.5 1554.17  5080.9 1555.72  5087.9 1555.29  5236.4 1557.18  5422.5 1557.78
#Mann=5,-1,0
  4731.3   0.035       0  4754.9    0.07       0  4986.5    0.07       0
  4990.8    0.07       0  5034.1   0.035       0
Bank Sta=4986.5,4990.8
Exp/Cntr=0.3,0.1

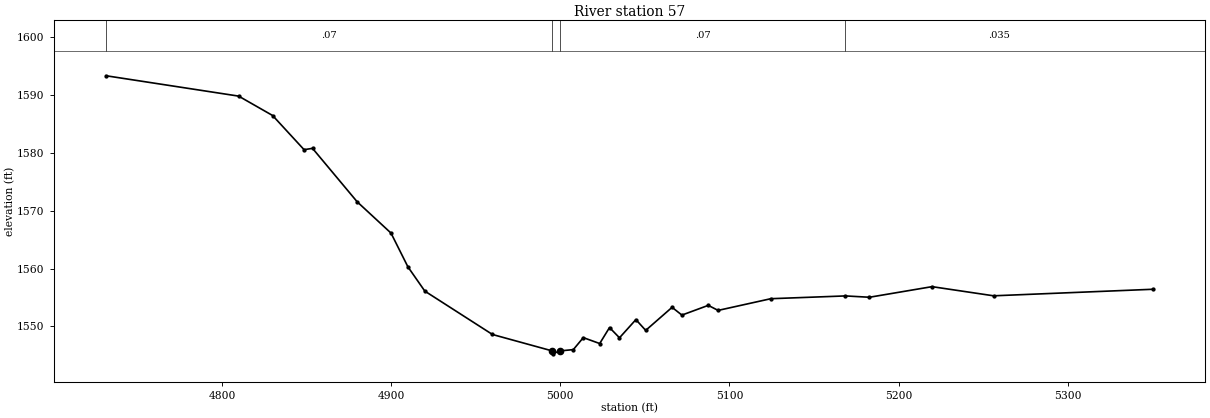
Type RM Length L Ch R = 1,57,0,0,0
BEGIN DESCRIPTION:
Chimney Creek 1106 1.0
END DESCRIPTION:
XS GIS Cut Line= 3
      1626096.70      6957638.94      1626365.04      6957647.98
      1626544.80      6957347.08
#Sta/Elev= 30
  4731.5 1593.28  4809.8 1589.77  4829.9 1586.42  4848.5 1580.52  4853.5 1580.75
  4879.9 1571.52  4899.9 1566.12  4909.9 1560.29  4919.9 1556.10  4959.9 1548.61
  4995.3 1545.77  4995.6 1545.27  4999.6 1545.77  5007.7 1546.00  5013.6 1548.07
  5023.3 1547.05  5029.1 1549.81  5035.0 1548.04  5044.7 1551.18  5050.5 1549.32
  5066.1 1553.30  5071.9 1551.96  5087.5 1553.64  5093.3 1552.77  5124.5 1554.79
  5168.6 1555.27  5182.8 1555.04  5219.8 1556.87  5256.2 1555.29  5350.5 1556.42
#Mann=4,-1,0
  4731.5    0.07       0  4995.3    0.07       0  4999.6    0.07       0
  5168.6   0.035       0
Bank Sta=4995.3,4999.6
Exp/Cntr=0.3,0.1

Chan Stop Cuts=-1