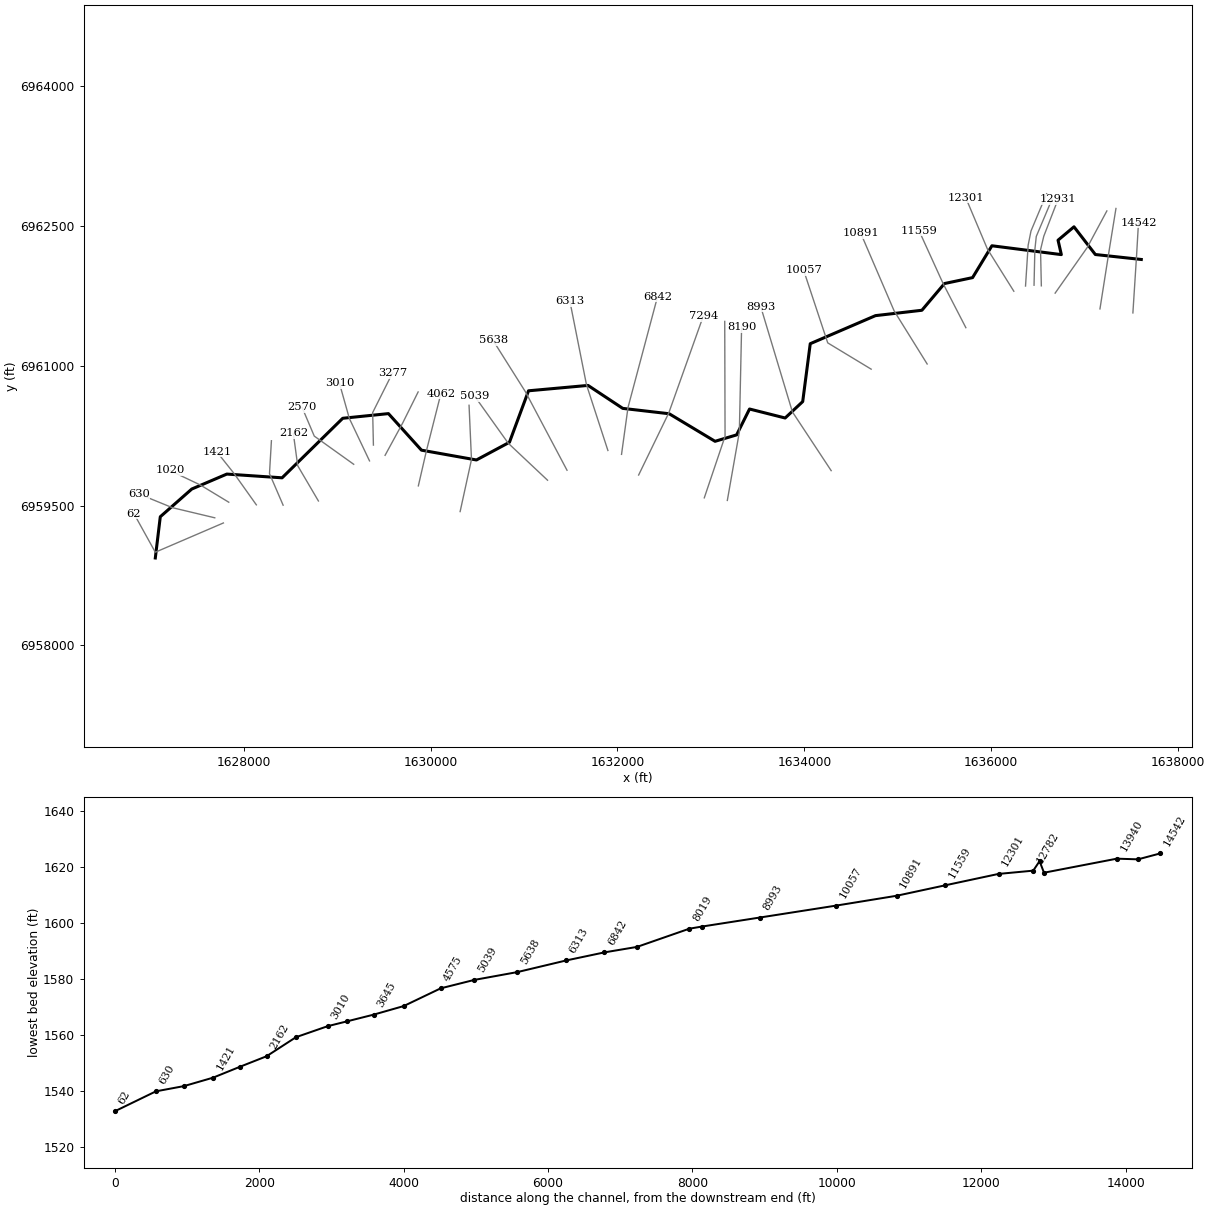
--- Chimney Creek 1107.prj (project) ---

Proj Title=Chimney Creek 1107 Base Level Engineering
Current Plan=p01
Default Exp/Contr=0.3,0.1
English Units
Geom File=g01
Flow File=f01
Plan File=p01
BEGIN DESCRIPTION:
Chimney Creek 1107
END DESCRIPTION:

--- Chimney Creek 1107.p01 (plan) ---

Plan Title=Multiple Run
Short Identifier=Multiple
Geom File=g01
Flow File=f01
Subcritical Flow
K Sum by GR= 0
Std Step Tol= 0.01
Critical Tol= 0.01
Num of Std Step Trials= 20
Max Error Tol= 0.3
Flow Tol Ratio= 0.001
Split Flow NTrial= 30
Split Flow Tol= 0.02
Split Flow Ratio= 0.02
Log Output Level= 0
Friction Slope Method= 1
Unsteady Friction Slope Method= 2
Unsteady Bridges Friction Slope Method= 1
Parabolic Critical Depth
Global Vel Dist=  1 , 1 , 1
Global Log Level= 0
CheckData=True
Encroach Param= -1, 0, 0, 0
BEGIN DESCRIPTION:
Multiple Run
END DESCRIPTION:

--- Chimney Creek 1107.f01 (steady flow) ---

Flow Title=Multiple
Number of Profiles=7
Profile Names=10-year,25-year,50-year,1pct_min,100-year,1pct_plu,500-year
River Rch & RM= Chimney Creek 11,Reach-1,14542
     352     491     608     374     746    1487    1137
River Rch & RM= Chimney Creek 11,Reach-1,8190
     463     656     819     508    1013    2022    1572
River Rch & RM= Chimney Creek 11,Reach-1,3010
     532     760     954     595    1187    2368    1860
Boundary for River Rch & Prof#=Chimney Creek 11,Reach-1,1
Up Type=0
Dn Type=3
Dn Slope=0.005
Boundary for River Rch & Prof#=Chimney Creek 11,Reach-1,2
Up Type=0
Dn Type=3
Dn Slope=0.005
Boundary for River Rch & Prof#=Chimney Creek 11,Reach-1,3
Up Type=0
Dn Type=3
Dn Slope=0.005
Boundary for River Rch & Prof#=Chimney Creek 11,Reach-1,4
Up Type=0
Dn Type=3
Dn Slope=0.005
Boundary for River Rch & Prof#=Chimney Creek 11,Reach-1,5
Up Type=0
Dn Type=3
Dn Slope=0.005
Boundary for River Rch & Prof#=Chimney Creek 11,Reach-1,6
Up Type=0
Dn Type=3
Dn Slope=0.005
Boundary for River Rch & Prof#=Chimney Creek 11,Reach-1,7
Up Type=0
Dn Type=3
Dn Slope=0.005

--- Chimney Creek 1107.g01 (geometry) ---

Geom Title=Existing Conditions

River Reach=Chimney Creek 11,Reach-1
Reach XY= 30
      1637605.00      6962138.00      1637113.33      6962191.13
      1636884.91      6962488.12      1636714.25      6962344.55
      1636749.56      6962190.05      1636006.62      6962284.88
      1635799.75      6961943.44      1635498.93      6961879.89
      1635257.45      6961593.46      1634760.86      6961535.92
      1634062.85      6961235.07      1633982.16      6960614.48
      1633794.38      6960438.60      1633413.28      6960534.95
      1633275.21      6960257.59      1633044.31      6960188.76
      1632553.45      6960484.25      1632056.55      6960541.75
      1631684.97      6960787.94      1631048.50      6960730.27
      1630844.24      6960178.32      1630491.08      6959988.68
      1629902.69      6960093.83      1629549.50      6960485.66
      1629060.52      6960435.64      1628411.62      6959797.41
      1627820.22      6959837.48      1627445.32      6959677.24
      1627108.24      6959379.99      1627055.00      6958938.00

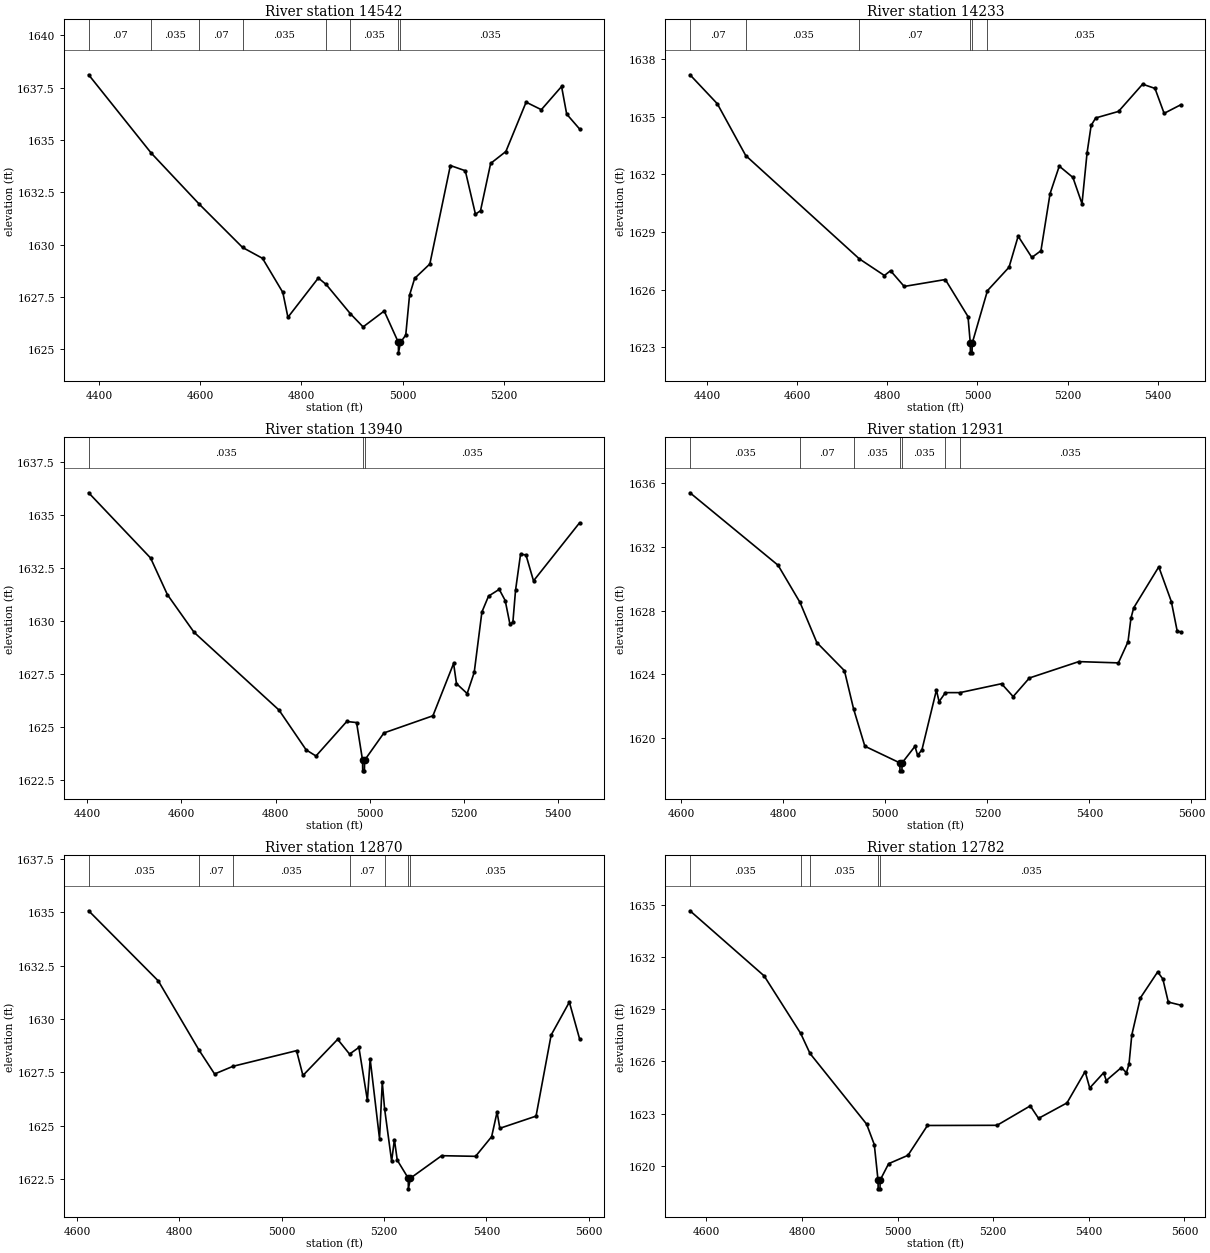
Type RM Length L Ch R = 1,14542,309,309,309
BEGIN DESCRIPTION:
Chimney Creek 1107 29.0
END DESCRIPTION:
XS GIS Cut Line= 3
      1637515.20      6961564.95      1637555.00      6962188.00
      1637575.08      6962533.40
#Sta/Elev= 30
  4379.5 1638.12  4503.0 1634.38  4598.6 1631.92  4683.8 1629.86  4723.2 1629.34
  4763.3 1627.71  4773.4 1626.52  4833.5 1628.40  4849.0 1628.09  4896.9 1626.69
  4922.0 1626.06  4963.7 1626.82  4991.7 1625.32  4991.9 1624.82  4995.9 1625.32
  5006.3 1625.67  5013.8 1627.58  5023.9 1628.38  5053.9 1629.07  5094.5 1633.78
  5124.0 1633.53  5144.1 1631.45  5154.1 1631.62  5174.1 1633.88  5204.2 1634.45
  5244.2 1636.81  5274.3 1636.45  5314.3 1637.56  5324.4 1636.24  5349.8 1635.53
#Mann=8,-1,0
  4379.5    0.07       0  4503.0   0.035       0  4598.6    0.07       0
  4683.8   0.035       0  4849.0    0.07       0  4896.9   0.035       0
  4991.7   0.035       0  4995.9   0.035       0
Bank Sta=4991.7,4995.9
Exp/Cntr=0.3,0.1

Type RM Length L Ch R = 1,14233,293,293,293
BEGIN DESCRIPTION:
Mapping XS c44665b1
END DESCRIPTION:
XS GIS Cut Line= 3
      1637162.78      6961607.99      1637262.60      6962243.82
      1637333.93      6962684.77
#Sta/Elev= 30
  4361.5 1637.19  4422.2 1635.68  4485.3 1632.98  4737.5 1627.60  4793.3 1626.73
  4806.9 1626.98  4837.3 1626.16  4928.6 1626.52  4979.0 1624.59  4984.1 1623.20
  4984.3 1622.70  4988.0 1622.70  4988.3 1623.20  5022.2 1625.94  5070.1 1627.16
  5090.4 1628.78  5120.8 1627.67  5141.0 1628.02  5161.3 1631.00  5181.7 1632.43
  5212.0 1631.84  5232.2 1630.47  5243.4 1633.11  5252.5 1634.55  5262.6 1634.94
  5313.3 1635.28  5366.8 1636.70  5394.3 1636.48  5414.6 1635.18  5451.8 1635.63
#Mann=6,-1,0
  4361.5    0.07       0  4485.3   0.035       0  4737.5    0.07       0
  4984.1    0.07       0  4988.3    0.07       0  5022.2   0.035       0
Bank Sta=4984.1,4988.3
Exp/Cntr=0.3,0.1

Type RM Length L Ch R = 1,13940,1009,1009,1009
BEGIN DESCRIPTION:
Mapping XS 57664b1a
END DESCRIPTION:
XS GIS Cut Line= 3
      1636683.16      6961777.22      1637026.06      6962265.52
      1637236.55      6962658.30
#Sta/Elev= 30
  4403.0 1636.07  4534.5 1632.99  4570.2 1631.26  4626.9 1629.48  4807.2 1625.81
  4864.8 1623.93  4885.7 1623.64  4951.0 1625.27  4971.9 1625.22  4984.6 1623.44
  4984.9 1622.94  4988.6 1622.94  4988.9 1623.44  5030.0 1624.73  5134.0 1625.54
  5177.9 1628.01  5184.0 1627.06  5206.7 1626.59  5221.7 1627.59  5238.0 1630.44
  5252.1 1631.19  5274.8 1631.51  5287.5 1630.98  5297.5 1629.87  5303.8 1629.96
  5309.4 1631.46  5320.0 1633.16  5331.5 1633.14  5347.6 1631.91  5445.3 1634.65
#Mann=3,-1,0
  4403.0   0.035       0  4984.6   0.035       0  4988.9   0.035       0
Bank Sta=4984.6,4988.9
Exp/Cntr=0.3,0.1

Type RM Length L Ch R = 1,12931,61,61,61
BEGIN DESCRIPTION:
Mapping XS b5c061cc
END DESCRIPTION:
XS GIS Cut Line= 4
      1636535.60      6961855.34      1636526.92      6962241.65
      1636561.65      6962387.05      1636715.08      6962784.68
#Sta/Elev= 30
  4617.2 1635.41  4789.9 1630.85  4832.9 1628.51  4865.8 1625.99  4919.9 1624.22
  4937.8 1621.82  4959.9 1619.47  5028.5 1618.42  5028.8 1617.92  5032.6 1617.92
  5032.9 1618.42  5058.1 1619.46  5063.3 1618.90  5071.8 1619.24  5100.2 1623.00
  5105.4 1622.27  5117.8 1622.84  5146.4 1622.84  5227.8 1623.40  5250.6 1622.59
  5282.4 1623.76  5379.2 1624.79  5456.8 1624.71  5475.7 1626.04  5481.4 1627.51
  5486.8 1628.17  5536.0 1630.75  5560.6 1628.57  5572.1 1626.71  5579.3 1626.65
#Mann=7,-1,0
  4617.2   0.035       0  4832.9    0.07       0  4937.8   0.035       0
  5028.5   0.035       0  5032.9   0.035       0  5117.8    0.07       0
  5146.4   0.035       0
Bank Sta=5028.5,5032.9
Exp/Cntr=0.3,0.1

Type RM Length L Ch R = 1,12870,88,88,88
BEGIN DESCRIPTION:
Mapping XS fe9df20a
END DESCRIPTION:
XS GIS Cut Line= 4
      1636457.48      6961861.87      1636466.16      6962241.65
      1636481.35      6962384.88      1636650.62      6962786.34
#Sta/Elev= 30
  4622.5 1635.06  4758.7 1631.78  4837.9 1628.56  4868.7 1627.43  4904.8 1627.79
  5028.9 1628.52  5041.4 1627.36  5109.3 1629.05  5132.5 1628.36  5150.8 1628.67
  5167.4 1626.20  5172.8 1628.13  5191.1 1624.41  5196.5 1627.04  5201.0 1625.81
  5214.8 1623.35  5220.2 1624.36  5225.8 1623.40  5247.2 1622.56  5247.5 1622.06
  5251.6 1622.56  5312.6 1623.61  5378.9 1623.58  5410.3 1624.50  5420.9 1625.65
  5426.3 1624.89  5497.1 1625.46  5526.6 1629.25  5562.2 1630.79  5582.1 1629.08
#Mann=7,-1,0
  4622.5   0.035       0  4837.9    0.07       0  4904.8   0.035       0
  5132.5    0.07       0  5201.0   0.035       0  5247.2   0.035       0
  5251.6   0.035       0
Bank Sta=5247.2,5251.6
Exp/Cntr=0.3,0.1

Type RM Length L Ch R = 1,12782,481,481,481
BEGIN DESCRIPTION:
Mapping XS b93e86c1
END DESCRIPTION:
XS GIS Cut Line= 4
      1636366.34      6961853.23      1636394.55      6962291.56
      1636424.93      6962443.47      1636592.02      6962842.76
#Sta/Elev= 30
  4565.5 1634.68  4720.6 1630.93  4797.2 1627.61  4816.6 1626.46  4935.0 1622.39
  4951.1 1621.21  4958.9 1619.16  4959.2 1618.66  4963.0 1618.66  4963.3 1619.16
  4981.1 1620.11  5021.5 1620.59  5062.3 1622.31  5207.9 1622.32  5277.4 1623.44
  5294.7 1622.72  5354.2 1623.61  5392.2 1625.42  5401.8 1624.47  5431.0 1625.35
  5436.4 1624.90  5468.1 1625.65  5478.6 1625.35  5484.0 1625.85  5489.8 1627.52
  5507.8 1629.66  5544.0 1631.16  5554.8 1630.75  5566.2 1629.42  5592.5 1629.24
#Mann=5,-1,0
  4565.5   0.035       0  4797.2    0.07       0  4816.6   0.035       0
  4958.9   0.035       0  4963.3   0.035       0
Bank Sta=4958.9,4963.3
Exp/Cntr=0.3,0.1

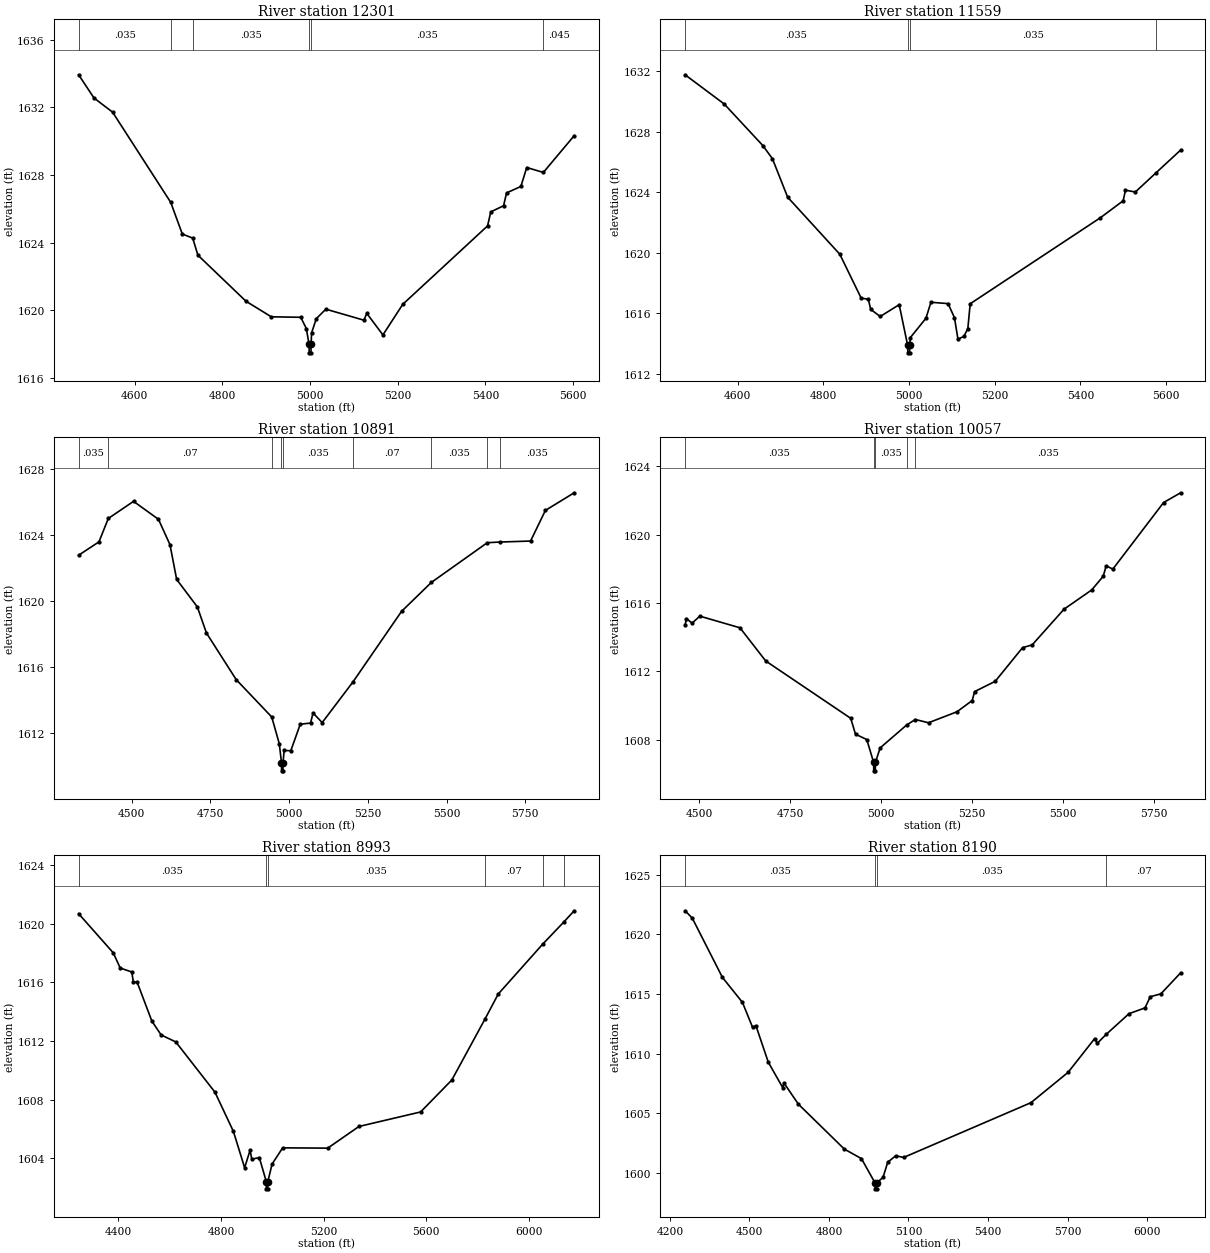
Type RM Length L Ch R = 1,12301,742,742,742
BEGIN DESCRIPTION:
Mapping XS 75c42ba8
END DESCRIPTION:
XS GIS Cut Line= 3
      1636241.19      6961797.49      1635959.07      6962248.88
      1635726.88      6962800.06
#Sta/Elev= 30
  4472.1 1633.92  4507.1 1632.55  4549.6 1631.71  4682.2 1626.38  4708.6 1624.51
  4732.3 1624.27  4744.2 1623.26  4853.8 1620.54  4911.6 1619.62  4978.8 1619.59
  4991.6 1618.92  4997.7 1617.99  4998.1 1617.49  5002.1 1617.49  5002.4 1617.99
  5003.5 1618.67  5014.3 1619.51  5036.0 1620.07  5122.8 1619.42  5129.5 1619.82
  5166.2 1618.55  5211.6 1620.36  5404.9 1624.99  5412.3 1625.82  5441.4 1626.18
  5448.3 1626.94  5480.9 1627.32  5494.3 1628.44  5532.2 1628.15  5602.5 1630.32
#Mann=6,-1,0
  4472.1   0.035       0  4682.2    0.07       0  4732.3   0.035       0
  4997.7   0.035       0  5002.4   0.035       0  5532.2   0.045       0
Bank Sta=4997.7,5002.4
Exp/Cntr=0.3,0.1

Type RM Length L Ch R = 1,11559,668,668,668
BEGIN DESCRIPTION:
Mapping XS 9f49b797
END DESCRIPTION:
XS GIS Cut Line= 3
      1635727.75      6961406.83      1635486.41      6961875.62
      1635225.99      6962448.55
#Sta/Elev= 30
  4477.3 1631.76  4568.6 1629.83  4658.6 1627.09  4681.1 1626.22  4716.6 1623.68
  4838.4 1619.91  4888.3 1617.01  4904.9 1616.94  4910.5 1616.27  4932.7 1615.80
  4977.0 1616.58  4996.7 1613.90  4997.1 1613.40  5001.3 1613.40  5001.6 1613.90
  5003.1 1614.41  5039.4 1615.68  5051.1 1616.74  5091.1 1616.65  5106.0 1615.72
  5114.1 1614.31  5128.0 1614.48  5137.2 1615.00  5142.7 1616.64  5446.6 1622.32
  5499.7 1623.44  5505.2 1624.14  5528.2 1624.02  5575.4 1625.26  5633.9 1626.79
#Mann=4,-1,0
  4477.3   0.035       0  4996.7   0.035       0  5001.6   0.035       0
  5575.4    0.07       0
Bank Sta=4996.7,5001.6
Exp/Cntr=0.3,0.1

Type RM Length L Ch R = 1,10891,834,834,834
BEGIN DESCRIPTION:
Mapping XS 062b4ba0
END DESCRIPTION:
XS GIS Cut Line= 3
      1635313.77      6961017.70      1634960.94      6961585.74
      1634604.13      6962417.43
#Sta/Elev= 30
  4331.3 1622.78  4395.9 1623.59  4425.5 1625.01  4505.7 1626.05  4584.8 1624.96
  4621.4 1623.42  4642.6 1621.31  4708.4 1619.64  4737.1 1618.06  4831.6 1615.23
  4944.5 1612.96  4968.6 1611.33  4975.5 1610.19  4975.9 1609.69  4980.1 1609.69
  4980.5 1610.19  4983.9 1610.93  5005.1 1610.91  5035.1 1612.52  5067.7 1612.59
  5075.8 1613.20  5104.8 1612.62  5202.6 1615.09  5356.8 1619.37  5451.6 1621.13
  5629.1 1623.54  5669.7 1623.58  5766.5 1623.64  5813.6 1625.50  5905.0 1626.57
#Mann=9,-1,0
  4331.3   0.035       0  4425.5    0.07       0  4944.5   0.035       0
  4975.5   0.035       0  4980.5   0.035       0  5202.6    0.07       0
  5451.6   0.035       0  5629.1    0.07       0  5669.7   0.035       0
Bank Sta=4975.5,4980.5
Exp/Cntr=0.3,0.1

Type RM Length L Ch R = 1,10057,1064,1064,1064
BEGIN DESCRIPTION:
Mapping XS 045c65ef
END DESCRIPTION:
XS GIS Cut Line= 3
      1634714.78      6960962.08      1634249.94      6961243.89
      1633992.13      6962022.53
#Sta/Elev= 30
  4460.8 1614.71  4464.5 1615.09  4480.0 1614.82  4501.3 1615.23  4611.8 1614.55
  4682.7 1612.61  4916.6 1609.26  4929.8 1608.33  4960.8 1608.02  4979.6 1606.69
  4980.0 1606.19  4984.3 1606.19  4984.7 1606.69  4997.6 1607.53  5070.6 1608.87
  5094.4 1609.19  5130.7 1609.00  5208.9 1609.64  5251.0 1610.30  5257.5 1610.82
  5314.2 1611.42  5389.6 1613.39  5416.0 1613.55  5503.8 1615.64  5579.8 1616.76
  5611.5 1617.56  5619.7 1618.17  5638.0 1617.98  5777.7 1621.87  5824.6 1622.44
#Mann=5,-1,0
  4460.8   0.035       0  4979.6   0.035       0  4984.7   0.035       0
  5070.6    0.07       0  5094.4   0.035       0
Bank Sta=4979.6,4984.7
Exp/Cntr=0.3,0.1

Type RM Length L Ch R = 1,8993,803,803,803
BEGIN DESCRIPTION:
Mapping XS 01275320
END DESCRIPTION:
XS GIS Cut Line= 3
      1634286.77      6959874.24      1633871.70      6960504.56
      1633533.27      6961631.22
#Sta/Elev= 30
  4245.3 1620.69  4380.2 1618.02  4407.3 1616.98  4452.5 1616.71  4458.5 1616.03
  4473.6 1616.00  4530.8 1613.35  4566.9 1612.41  4624.1 1611.93  4776.6 1608.50
  4848.5 1605.82  4892.2 1603.34  4913.3 1604.53  4920.3 1603.92  4949.4 1604.04
  4976.5 1602.40  4977.0 1601.90  4982.2 1601.90  4982.7 1602.40  4999.1 1603.59
  5040.4 1604.70  5216.1 1604.68  5337.7 1606.16  5577.9 1607.15  5699.5 1609.33
  5828.4 1613.48  5880.7 1615.21  6054.2 1618.62  6137.0 1620.14  6176.4 1620.89
#Mann=6,-1,0
  4245.3   0.035       0  4976.5   0.035       0  4982.7   0.035       0
  5828.4    0.07       0  6054.2   0.035       0  6137.0    0.07       0
Bank Sta=4976.5,4982.7
Exp/Cntr=0.3,0.1

Type RM Length L Ch R = 1,8190,171,171,171
BEGIN DESCRIPTION:
Mapping XS 9f918cde
END DESCRIPTION:
XS GIS Cut Line= 3
      1633175.64      6959554.85      1633304.11      6960287.47
      1633328.41      6961412.51
#Sta/Elev= 30
  4257.5 1621.97  4284.4 1621.36  4398.2 1616.39  4473.9 1614.29  4511.9 1612.21
  4524.7 1612.34  4571.3 1609.28  4625.6 1607.16  4630.7 1607.53  4685.0 1605.76
  4858.2 1602.00  4922.7 1601.20  4973.8 1599.17  4974.3 1598.67  4979.6 1598.67
  4980.1 1599.17  5004.1 1599.63  5021.8 1600.90  5051.8 1601.44  5081.9 1601.30
  5562.0 1605.89  5702.0 1608.43  5802.0 1611.25  5812.0 1610.86  5846.6 1611.63
  5932.0 1613.35  5992.1 1613.83  6012.1 1614.77  6052.1 1615.01  6126.6 1616.77
#Mann=4,-1,0
  4257.5   0.035       0  4973.8   0.035       0  4980.1   0.035       0
  5846.6    0.07       0
Bank Sta=4973.8,4980.1
Exp/Cntr=0.3,0.1

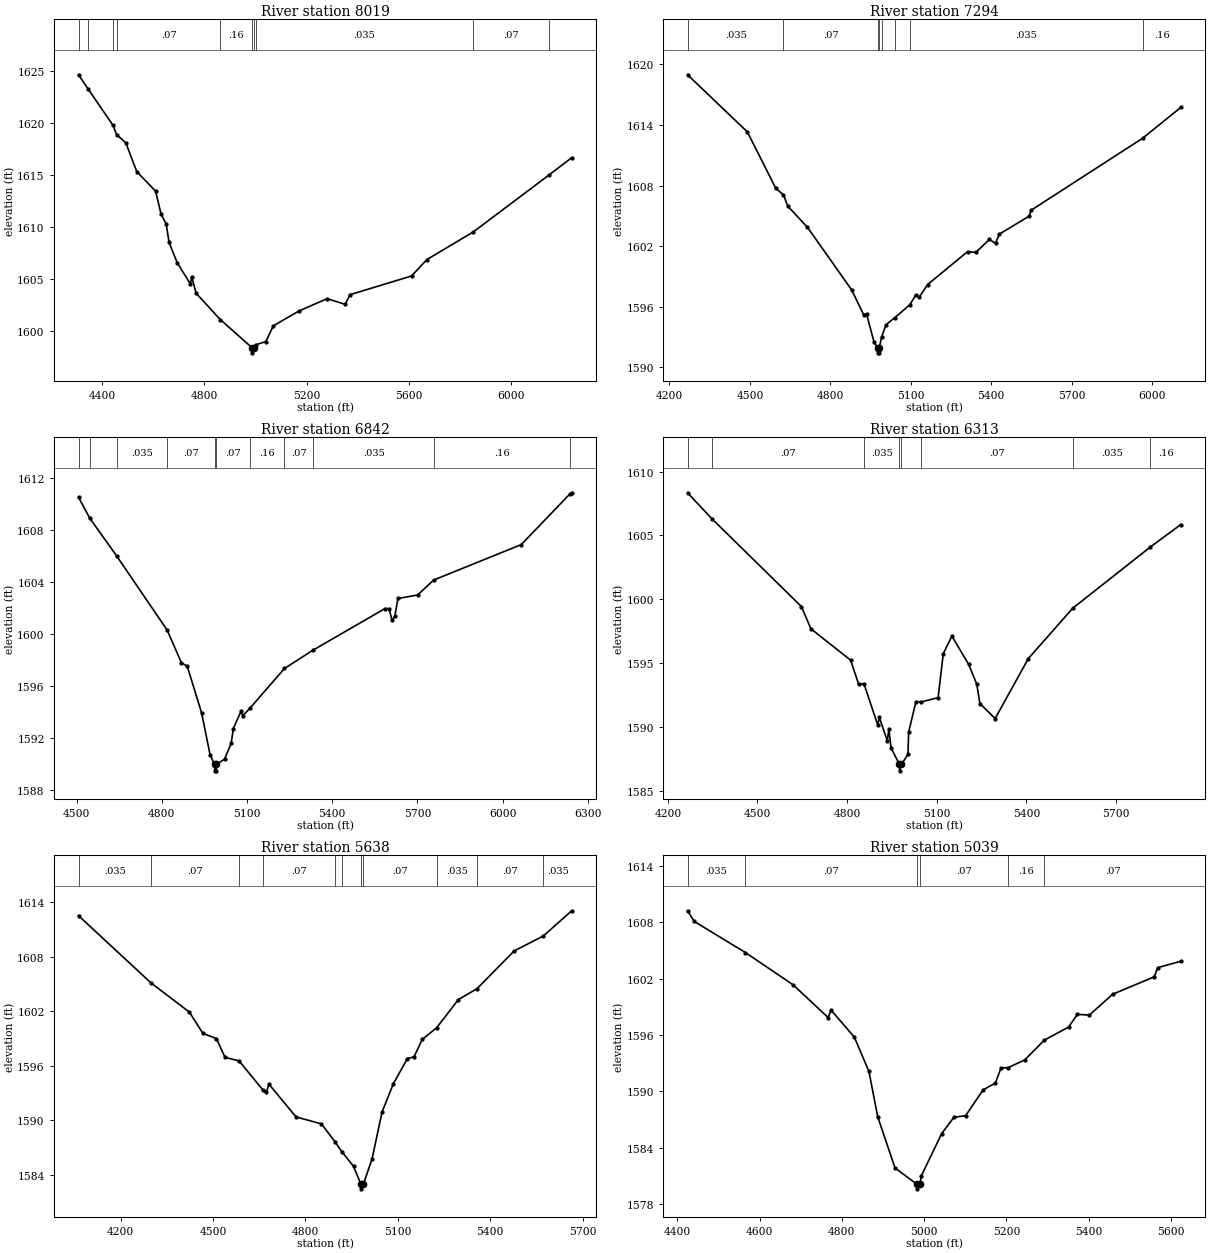
Type RM Length L Ch R = 1,8019,725,725,725
BEGIN DESCRIPTION:
Mapping XS dfce5b9d
END DESCRIPTION:
XS GIS Cut Line= 3
      1632929.09      6959582.56      1633151.33      6960242.33
      1633147.86      6961473.94
#Sta/Elev= 30
  4308.0 1624.62  4346.0 1623.24  4443.2 1619.75  4457.1 1618.87  4493.1 1618.09
  4535.4 1615.33  4609.2 1613.45  4630.3 1611.28  4650.8 1610.28  4662.0 1608.52
  4693.6 1606.58  4745.3 1604.53  4750.5 1605.23  4767.5 1603.65  4862.0 1601.12
  4985.9 1598.42  4986.4 1597.92  4992.2 1598.42  5000.3 1598.69  5039.9 1599.00
  5069.9 1600.52  5169.9 1601.94  5279.9 1603.12  5349.9 1602.58  5369.9 1603.51
  5609.9 1605.30  5669.9 1606.88  5851.1 1609.53  6146.1 1614.98  6235.8 1616.66
#Mann=10,-1,0
  4308.0   0.035       0  4346.0    0.07       0  4443.2   0.035       0
  4457.1    0.07       0  4862.0    0.16       0  4985.9    0.07       0
  4992.2    0.16       0  5000.3   0.035       0  5851.1    0.07       0
  6146.1    0.16       0
Bank Sta=4985.9,4992.2
Exp/Cntr=0.3,0.1

Type RM Length L Ch R = 1,7294,452,452,452
BEGIN DESCRIPTION:
Mapping XS 1bdf03f7
END DESCRIPTION:
XS GIS Cut Line= 3
      1632226.66      6959827.35      1632549.59      6960494.06
      1632917.64      6961528.75
#Sta/Elev= 30
  4267.6 1618.98  4490.5 1613.32  4596.3 1607.74  4625.3 1607.07  4641.4 1605.95
  4714.7 1603.86  4879.4 1597.65  4923.9 1595.21  4935.0 1595.27  4963.1 1592.46
  4976.2 1591.91  4976.7 1591.41  4982.2 1591.41  4982.7 1591.91  4990.9 1592.95
  5007.8 1594.21  5040.8 1594.90  5096.7 1596.19  5118.7 1597.15  5131.8 1596.94
  5162.6 1598.18  5311.5 1601.44  5342.4 1601.37  5393.4 1602.66  5415.9 1602.26
  5429.6 1603.17  5542.3 1604.98  5547.6 1605.53  5964.1 1612.68  6106.6 1615.74
#Mann=8,-1,0
  4267.6   0.035       0  4625.3    0.07       0  4976.2    0.07       0
  4982.7    0.07       0  4990.9    0.16       0  5040.8    0.07       0
  5096.7   0.035       0  5964.1    0.16       0
Bank Sta=4976.2,4982.7
Exp/Cntr=0.3,0.1

Type RM Length L Ch R = 1,6842,529,529,529
BEGIN DESCRIPTION:
Mapping XS 07547d26
END DESCRIPTION:
XS GIS Cut Line= 3
      1632043.57      6960048.67      1632113.02      6960552.17
      1632429.00      6961739.69
#Sta/Elev= 30
  4506.4 1610.51  4546.5 1608.89  4641.2 1605.98  4818.5 1600.29  4869.1 1597.76
  4889.3 1597.51  4939.8 1593.92  4970.1 1590.65  4985.6 1589.95  4986.1 1589.45
  4991.6 1589.45  4992.1 1589.95  5020.7 1590.35  5044.2 1591.58  5051.7 1592.71
  5079.2 1594.06  5084.3 1593.68  5110.9 1594.29  5231.7 1597.33  5333.7 1598.76
  5585.5 1601.94  5600.2 1601.94  5610.5 1601.05  5620.4 1601.34  5631.2 1602.72
  5700.7 1602.99  5757.2 1604.14  6065.8 1606.87  6238.5 1610.80  6243.5 1610.86
#Mann=11,-1,0
  4506.4   0.035       0  4546.5    0.07       0  4641.2   0.035       0
  4818.5    0.07       0  4985.6    0.07       0  4992.1    0.07       0
  5110.9    0.16       0  5231.7    0.07       0  5333.7   0.035       0
  5757.2    0.16       0  6238.5    0.07       0
Bank Sta=4985.6,4992.1
Exp/Cntr=0.3,0.1

Type RM Length L Ch R = 1,6313,675,675,675
BEGIN DESCRIPTION:
Mapping XS 6249034d
END DESCRIPTION:
XS GIS Cut Line= 3
      1631897.74      6960090.37      1631668.58      6960795.22
      1631491.50      6961687.55
#Sta/Elev= 30
  4266.0 1608.34  4347.4 1606.31  4647.1 1599.43  4679.0 1597.69  4812.0 1595.23
  4838.7 1593.35  4856.3 1593.40  4902.6 1590.16  4907.9 1590.75  4934.6 1588.93
  4939.8 1589.85  4947.0 1588.38  4975.2 1587.07  4975.7 1586.57  4981.8 1587.07
  5003.7 1587.85  5006.0 1589.59  5030.4 1591.99  5048.9 1591.97  5104.7 1592.30
  5122.1 1595.75  5150.8 1597.12  5207.1 1594.90  5234.3 1593.34  5244.5 1591.84
  5295.5 1590.66  5406.7 1595.36  5555.2 1599.30  5815.5 1604.10  5916.9 1605.85
#Mann=8,-1,0
  4266.0   0.035       0  4347.4    0.07       0  4856.3   0.035       0
  4975.2   0.035       0  4981.8   0.035       0  5048.9    0.07       0
  5555.2   0.035       0  5815.5    0.16       0
Bank Sta=4975.2,4981.8
Exp/Cntr=0.3,0.1

Type RM Length L Ch R = 1,5638,599,599,599
BEGIN DESCRIPTION:
Mapping XS b003f066
END DESCRIPTION:
XS GIS Cut Line= 3
      1631460.23      6959878.57      1631015.80      6960718.83
      1630669.30      6961269.77
#Sta/Elev= 30
  4063.5 1612.54  4299.4 1605.11  4423.4 1601.91  4467.4 1599.56  4511.4 1598.99
  4539.1 1596.92  4584.6 1596.53  4661.3 1593.36  4673.7 1593.10  4681.8 1593.96
  4769.8 1590.35  4852.2 1589.58  4895.9 1587.63  4918.2 1586.52  4956.6 1584.90
  4980.4 1582.92  4980.9 1582.42  4988.2 1582.92  5016.5 1585.70  5049.1 1590.89
  5085.6 1593.99  5131.2 1596.78  5152.7 1596.97  5179.8 1598.90  5226.6 1600.19
  5296.6 1603.28  5357.4 1604.49  5477.7 1608.64  5573.0 1610.31  5664.9 1613.08
#Mann=11,-1,0
  4063.5   0.035       0  4299.4    0.07       0  4584.6    0.16       0
  4661.3    0.07       0  4895.9   0.035       0  4918.2    0.07       0
  4980.4    0.07       0  4988.2    0.07       0  5226.6   0.035       0
  5357.4    0.07       0  5573.0   0.035       0
Bank Sta=4980.4,4988.2
Exp/Cntr=0.3,0.1

Type RM Length L Ch R = 1,5039,464,464,464
BEGIN DESCRIPTION:
Mapping XS 80240e7e
END DESCRIPTION:
XS GIS Cut Line= 3
      1631251.86      6959771.66      1630830.84      6960168.80
      1630471.13      6960673.70
#Sta/Elev= 30
  4425.0 1609.24  4441.4 1608.10  4565.6 1604.79  4681.9 1601.34  4766.7 1597.86
  4774.0 1598.65  4830.6 1595.76  4865.8 1592.12  4887.3 1587.27  4929.3 1581.83
  4982.1 1580.11  4982.6 1579.61  4989.9 1580.11  4993.2 1581.00  5042.7 1585.50
  5072.2 1587.22  5101.0 1587.42  5143.5 1590.16  5173.1 1590.88  5187.0 1592.51
  5203.2 1592.51  5244.4 1593.34  5292.3 1595.46  5351.3 1596.85  5372.2 1598.20
  5401.7 1598.13  5458.3 1600.35  5559.1 1602.20  5567.6 1603.18  5623.7 1603.86
#Mann=6,-1,0
  4425.0   0.035       0  4565.6    0.07       0  4982.1    0.07       0
  4989.9    0.07       0  5203.2    0.16       0  5292.3    0.07       0
Bank Sta=4982.1,4989.9
Exp/Cntr=0.3,0.1

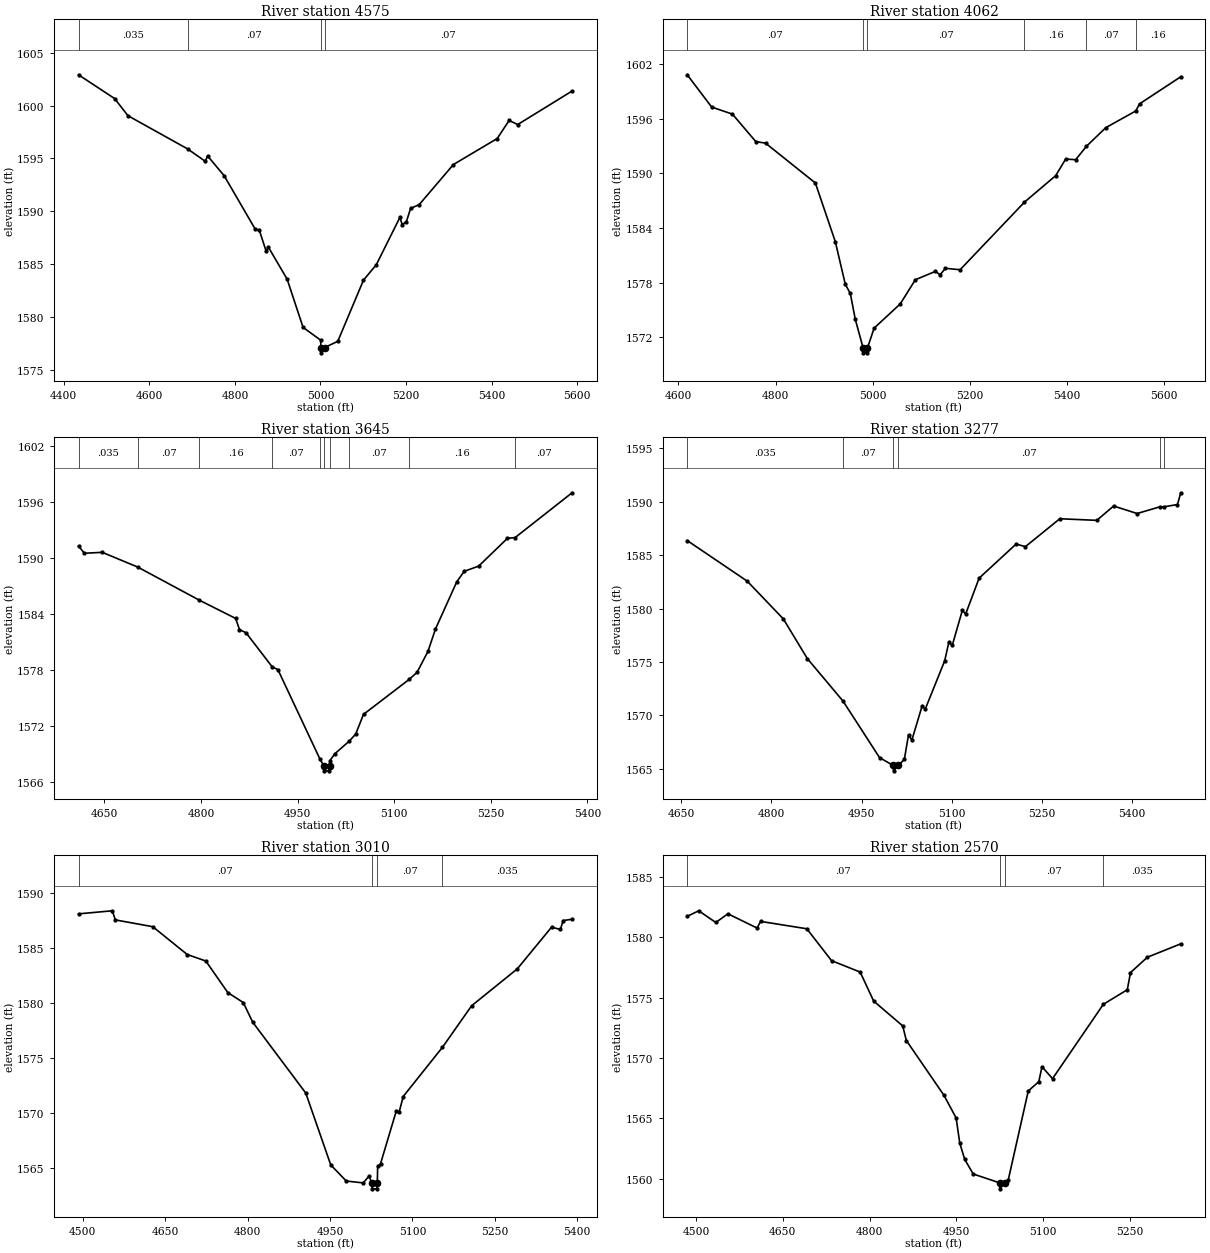
Type RM Length L Ch R = 1,4575,513,513,513
BEGIN DESCRIPTION:
Mapping XS 3a2eaa57
END DESCRIPTION:
XS GIS Cut Line= 3
      1630316.52      6959435.30      1630438.05      6959993.02
      1630412.09      6960574.93
#Sta/Elev= 30
  4434.6 1602.92  4519.2 1600.66  4550.0 1599.05  4689.3 1595.91  4730.9 1594.73
  4736.0 1595.25  4774.9 1593.37  4846.8 1588.36  4857.0 1588.22  4873.0 1586.23
  4878.1 1586.62  4922.1 1583.58  4959.3 1579.02  5000.3 1577.81  5001.1 1577.11
  5001.6 1576.61  5009.6 1577.11  5040.4 1577.70  5100.5 1583.49  5130.5 1584.95
  5185.8 1589.44  5190.8 1588.75  5200.6 1589.00  5210.6 1590.28  5230.6 1590.63
  5310.7 1594.43  5413.1 1596.89  5440.8 1598.60  5460.8 1598.21  5587.9 1601.38
#Mann=4,-1,0
  4434.6   0.035       0  4689.3    0.07       0  5001.1    0.07       0
  5009.6    0.07       0
Bank Sta=5001.1,5009.6
Exp/Cntr=0.3,0.1

Type RM Length L Ch R = 1,4062,417,417,417
BEGIN DESCRIPTION:
Mapping XS 21a4c233
END DESCRIPTION:
XS GIS Cut Line= 3
      1629869.46      6959710.87      1629956.28      6960088.51
      1630110.17      6960697.57
#Sta/Elev= 30
  4618.2 1600.86  4668.5 1597.31  4711.3 1596.53  4759.3 1593.51  4779.4 1593.34
  4882.0 1588.95  4923.1 1582.48  4943.6 1577.80  4953.9 1576.80  4964.1 1573.96
  4980.4 1570.77  4980.9 1570.27  4988.4 1570.27  4988.9 1570.77  5002.9 1572.99
  5056.6 1575.65  5087.7 1578.31  5128.9 1579.23  5138.7 1578.86  5149.6 1579.57
  5179.8 1579.41  5312.3 1586.85  5376.5 1589.76  5397.1 1591.59  5417.7 1591.52
  5439.8 1592.99  5479.6 1595.04  5541.4 1596.88  5549.1 1597.66  5633.9 1600.64
#Mann=6,-1,0
  4618.2    0.07       0  4980.4    0.07       0  4988.9    0.07       0
  5312.3    0.16       0  5439.8    0.07       0  5541.4    0.16       0
Bank Sta=4980.4,4988.9
Exp/Cntr=0.3,0.1

Type RM Length L Ch R = 1,3645,368,368,368
BEGIN DESCRIPTION:
Mapping XS 6b8dceaf
END DESCRIPTION:
XS GIS Cut Line= 3
      1629513.56      6960038.58      1629700.20      6960381.48
      1629867.31      6960717.86
#Sta/Elev= 30
  4610.1 1591.28  4619.3 1590.51  4646.9 1590.61  4702.0 1589.03  4797.7 1585.48
  4853.9 1583.53  4859.9 1582.34  4870.1 1581.99  4910.8 1578.33  4919.5 1578.05
  4985.0 1568.43  4991.2 1567.70  4991.7 1567.20  4999.3 1567.20  4999.8 1567.70
  5000.3 1568.30  5007.8 1569.02  5030.2 1570.38  5040.3 1571.14  5052.4 1573.25
  5123.2 1576.99  5135.5 1577.75  5152.4 1579.99  5164.1 1582.39  5197.2 1587.46
  5208.8 1588.58  5231.1 1589.13  5275.8 1592.11  5287.7 1592.19  5376.1 1596.99
#Mann=10,-1,0
  4610.1   0.035       0  4702.0    0.07       0  4797.7    0.16       0
  4910.8    0.07       0  4985.0    0.16       0  4991.2    0.07       0
  4999.8    0.16       0  5030.2    0.07       0  5123.2    0.16       0
  5287.7    0.07       0
Bank Sta=4991.2,4999.8
Exp/Cntr=0.3,0.1

Type RM Length L Ch R = 1,3277,267,267,267
BEGIN DESCRIPTION:
Mapping XS 41ca5f53
END DESCRIPTION:
XS GIS Cut Line= 3
      1629388.70      6960148.23      1629380.89      6960497.15
      1629591.84      6960919.05
#Sta/Elev= 30
  4660.1 1586.36  4759.9 1582.56  4819.9 1579.03  4859.9 1575.31  4919.3 1571.33
  4979.9 1566.05  5002.7 1565.31  5003.2 1564.81  5011.3 1565.31  5021.2 1565.89
  5028.1 1568.17  5033.7 1567.69  5050.5 1570.84  5056.1 1570.61  5088.3 1575.11
  5095.2 1576.86  5100.8 1576.54  5117.6 1579.82  5123.2 1579.49  5145.5 1582.84
  5207.0 1586.03  5222.5 1585.79  5279.7 1588.40  5341.2 1588.25  5369.2 1589.59
  5408.3 1588.89  5445.8 1589.51  5452.3 1589.51  5475.4 1589.73  5480.8 1590.83
#Mann=6,-1,0
  4660.1   0.035       0  4919.3    0.07       0  5002.7    0.07       0
  5011.3    0.07       0  5445.8    0.16       0  5452.3    0.07       0
Bank Sta=5002.7,5011.3
Exp/Cntr=0.3,0.1

Type RM Length L Ch R = 1,3010,440,440,440
BEGIN DESCRIPTION:
Mapping XS f50efb6d
END DESCRIPTION:
XS GIS Cut Line= 3
      1629347.05      6959978.89      1629130.89      6960434.65
      1629024.37      6960813.95
#Sta/Elev= 30
  4492.1 1588.11  4553.6 1588.39  4559.1 1587.56  4627.3 1586.94  4690.0 1584.41
  4723.8 1583.82  4763.8 1580.95  4792.0 1580.04  4809.2 1578.25  4905.7 1571.81
  4951.2 1565.27  4979.4 1563.80  5010.4 1563.63  5020.8 1564.24  5026.4 1563.59
  5026.9 1563.09  5035.5 1563.09  5036.0 1563.59  5036.6 1565.13  5041.8 1565.37
  5070.7 1570.20  5075.8 1570.08  5083.1 1571.49  5154.6 1575.97  5207.7 1579.75
  5290.7 1583.10  5353.2 1586.90  5369.2 1586.69  5374.4 1587.50  5390.5 1587.62
#Mann=4,-1,0
  4492.1    0.07       0  5026.4    0.07       0  5036.0    0.07       0
  5154.6   0.035       0
Bank Sta=5026.4,5036
Exp/Cntr=0.3,0.1

Type RM Length L Ch R = 1,2570,408,408,408
BEGIN DESCRIPTION:
Mapping XS b1012b85
END DESCRIPTION:
XS GIS Cut Line= 3
      1629177.72      6959942.49      1628755.89      6960244.54
      1628625.67      6960551.86
#Sta/Elev= 30
  4485.0 1581.73  4504.9 1582.19  4534.4 1581.22  4555.3 1581.94  4605.7 1580.76
  4611.8 1581.31  4691.6 1580.70  4734.3 1578.06  4783.8 1577.11  4807.1 1574.71
  4857.3 1572.65  4863.6 1571.44  4928.7 1566.89  4949.6 1565.02  4955.8 1562.95
  4964.4 1561.59  4979.1 1560.38  5024.5 1559.65  5025.0 1559.15  5034.2 1559.65
  5039.6 1559.88  5074.2 1567.26  5092.4 1568.03  5097.9 1569.27  5116.1 1568.28
  5203.9 1574.44  5245.3 1575.65  5250.8 1577.07  5279.9 1578.34  5337.6 1579.45
#Mann=4,-1,0
  4485.0    0.07       0  5024.5    0.07       0  5034.2    0.07       0
  5203.9   0.035       0
Bank Sta=5024.5,5034.2
Exp/Cntr=0.3,0.1

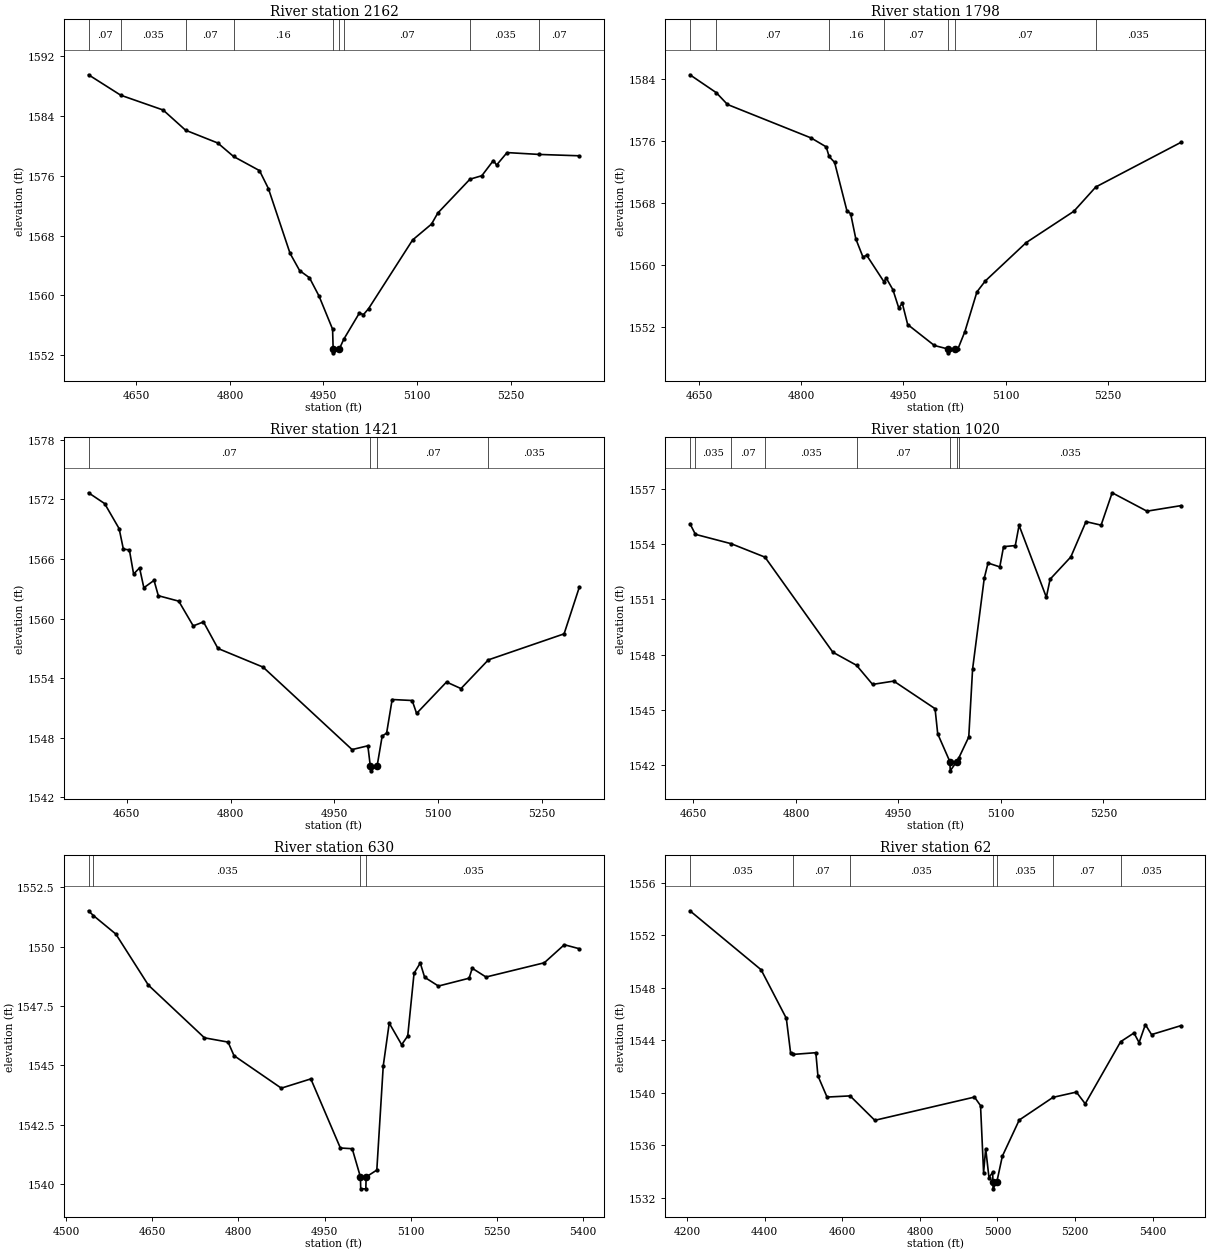
Type RM Length L Ch R = 1,2162,364,364,364
BEGIN DESCRIPTION:
Mapping XS 722b33f9
END DESCRIPTION:
XS GIS Cut Line= 3
      1628800.16      6959549.22      1628578.80      6959926.83
      1628531.95      6960273.07
#Sta/Elev= 30
  4573.3 1589.50  4624.9 1586.77  4692.9 1584.79  4728.9 1582.09  4780.5 1580.38
  4805.8 1578.58  4847.4 1576.69  4861.7 1574.29  4896.4 1565.63  4911.8 1563.32
  4927.5 1562.37  4942.8 1559.93  4964.6 1555.49  4965.5 1552.83  4966.0 1552.33
  4975.3 1552.83  4982.4 1554.13  5007.6 1557.66  5014.1 1557.44  5022.3 1558.24
  5092.9 1567.42  5123.2 1569.54  5133.3 1571.02  5184.8 1575.54  5203.9 1576.01
  5222.4 1578.04  5227.5 1577.43  5244.3 1579.10  5296.1 1578.85  5360.4 1578.67
#Mann=9,-1,0
  4573.3    0.07       0  4624.9   0.035       0  4728.9    0.07       0
  4805.8    0.16       0  4965.5    0.07       0  4975.3    0.16       0
  4982.4    0.07       0  5184.8   0.035       0  5296.1    0.07       0
Bank Sta=4965.5,4975.3
Exp/Cntr=0.3,0.1

Type RM Length L Ch R = 1,1798,377,377,377
BEGIN DESCRIPTION:
Mapping XS 0ca55c15
END DESCRIPTION:
XS GIS Cut Line= 3
      1628422.56      6959504.07      1628276.72      6959842.63
      1628297.44      6960194.89
#Sta/Elev= 30
  4636.2 1584.56  4674.9 1582.25  4691.4 1580.72  4814.4 1576.39  4836.5 1575.24
  4840.7 1574.00  4848.8 1573.24  4866.9 1566.99  4872.4 1566.61  4880.0 1563.35
  4890.5 1561.00  4895.9 1561.24  4921.1 1557.84  4924.9 1558.25  4934.5 1556.78
  4943.0 1554.45  4948.4 1555.00  4956.2 1552.28  4995.4 1549.57  5015.3 1549.12
  5015.8 1548.62  5025.2 1549.12  5030.2 1549.16  5040.3 1551.37  5058.0 1556.50
  5070.3 1557.91  5130.4 1562.87  5200.5 1566.92  5232.7 1570.06  5357.7 1575.82
#Mann=7,-1,0
  4636.2   0.035       0  4674.9    0.07       0  4840.7    0.16       0
  4921.1    0.07       0  5015.3    0.07       0  5025.2    0.07       0
  5232.7   0.035       0
Bank Sta=5015.3,5025.2
Exp/Cntr=0.3,0.1

Type RM Length L Ch R = 1,1421,401,401,401
BEGIN DESCRIPTION:
Mapping XS d90bbd14
END DESCRIPTION:
XS GIS Cut Line= 3
      1628136.08      6959507.65      1627897.37      6959844.02
      1627712.92      6960076.21
#Sta/Elev= 30
  4594.8 1572.67  4618.1 1571.58  4639.0 1569.06  4645.1 1567.00  4653.8 1566.92
  4659.9 1564.49  4668.5 1565.11  4674.7 1563.11  4689.4 1563.85  4695.6 1562.31
  4725.1 1561.76  4746.0 1559.27  4760.8 1559.67  4781.7 1557.00  4846.9 1555.12
  4975.4 1546.82  4998.2 1547.20  5001.7 1545.18  5002.2 1544.68  5011.6 1545.18
  5018.9 1548.18  5025.3 1548.48  5033.3 1551.86  5062.2 1551.76  5068.6 1550.46
  5111.8 1553.62  5132.7 1552.96  5172.2 1555.85  5281.6 1558.47  5303.8 1563.21
#Mann=4,-1,0
  4594.8    0.07       0  5001.7    0.07       0  5011.6    0.07       0
  5172.2   0.035       0
Bank Sta=5001.7,5011.6
Exp/Cntr=0.3,0.1

Type RM Length L Ch R = 1,1020,390,390,390
BEGIN DESCRIPTION:
Mapping XS 704296a1
END DESCRIPTION:
XS GIS Cut Line= 3
      1627840.97      6959535.84      1627537.12      6959720.32
      1627209.71      6959876.44
#Sta/Elev= 30
  4645.0 1555.12  4653.0 1554.54  4705.4 1554.03  4754.8 1553.30  4854.1 1548.13
  4888.7 1547.42  4912.2 1546.38  4943.2 1546.56  5003.6 1545.06  5007.5 1543.69
  5025.3 1542.18  5025.8 1541.68  5035.2 1542.18  5038.6 1542.40  5052.9 1543.52
  5058.5 1547.21  5075.6 1552.16  5081.1 1552.98  5098.3 1552.77  5103.8 1553.87
  5121.0 1553.93  5126.5 1555.03  5166.4 1551.12  5171.9 1552.10  5202.2 1553.31
  5224.4 1555.23  5246.5 1555.04  5262.7 1556.80  5313.6 1555.80  5363.2 1556.10
#Mann=8,-1,0
  4645.0    0.07       0  4653.0   0.035       0  4705.4    0.07       0
  4754.8   0.035       0  4888.7    0.07       0  5025.3    0.07       0
  5035.2    0.07       0  5038.6   0.035       0
Bank Sta=5025.3,5035.2
Exp/Cntr=0.3,0.1

Type RM Length L Ch R = 1,630,568,568,568
BEGIN DESCRIPTION:
Mapping XS df55d3e5
END DESCRIPTION:
XS GIS Cut Line= 3
      1627691.17      6959368.77      1627237.64      6959477.27
      1626878.72      6959624.30
#Sta/Elev= 30
  4539.2 1551.51  4547.6 1551.31  4586.7 1550.53  4643.3 1548.38  4740.9 1546.16
  4782.0 1545.98  4792.3 1545.41  4874.6 1544.04  4926.0 1544.43  4977.4 1541.52
  4998.0 1541.49  5012.3 1540.30  5012.8 1539.80  5021.7 1539.80  5022.2 1540.30
  5040.8 1540.59  5052.0 1544.98  5062.4 1546.78  5084.0 1545.87  5094.6 1546.24
  5105.6 1548.88  5116.4 1549.31  5124.0 1548.71  5148.0 1548.34  5201.4 1548.67
  5206.8 1549.09  5230.8 1548.72  5332.2 1549.32  5367.0 1550.08  5393.4 1549.91
#Mann=4,-1,0
  4539.2    0.07       0  4547.6   0.035       0  5012.3   0.035       0
  5022.2   0.035       0
Bank Sta=5012.3,5022.2
Exp/Cntr=0.3,0.1

Type RM Length L Ch R = 1,62,0,0,0
BEGIN DESCRIPTION:
Chimney Creek 1107 1.0
END DESCRIPTION:
XS GIS Cut Line= 3
      1627783.45      6959313.43      1627054.98      6958999.84
      1626826.04      6959413.86
#Sta/Elev= 30
  4206.9 1553.87  4390.4 1549.38  4455.5 1545.68  4466.5 1543.05  4473.1 1542.93
  4531.6 1543.06  4537.0 1541.30  4560.5 1539.68  4620.0 1539.77  4683.7 1537.91
  4940.8 1539.68  4956.4 1539.03  4964.3 1533.92  4969.7 1535.75  4978.2 1533.54
  4987.8 1533.96  4988.3 1533.19  4988.8 1532.69  4998.2 1533.19  5012.7 1535.18
  5056.2 1537.93  5143.4 1539.66  5203.6 1540.06  5226.4 1539.17  5317.8 1543.90
  5352.1 1544.56  5365.4 1543.83  5381.5 1545.20  5397.5 1544.44  5473.1 1545.12
#Mann=7,-1,0
  4206.9   0.035       0  4473.1    0.07       0  4620.0   0.035       0
  4988.3   0.035       0  4998.2   0.035       0  5143.4    0.07       0
  5317.8   0.035       0
Bank Sta=4988.3,4998.2
Exp/Cntr=0.3,0.1

Chan Stop Cuts=-1