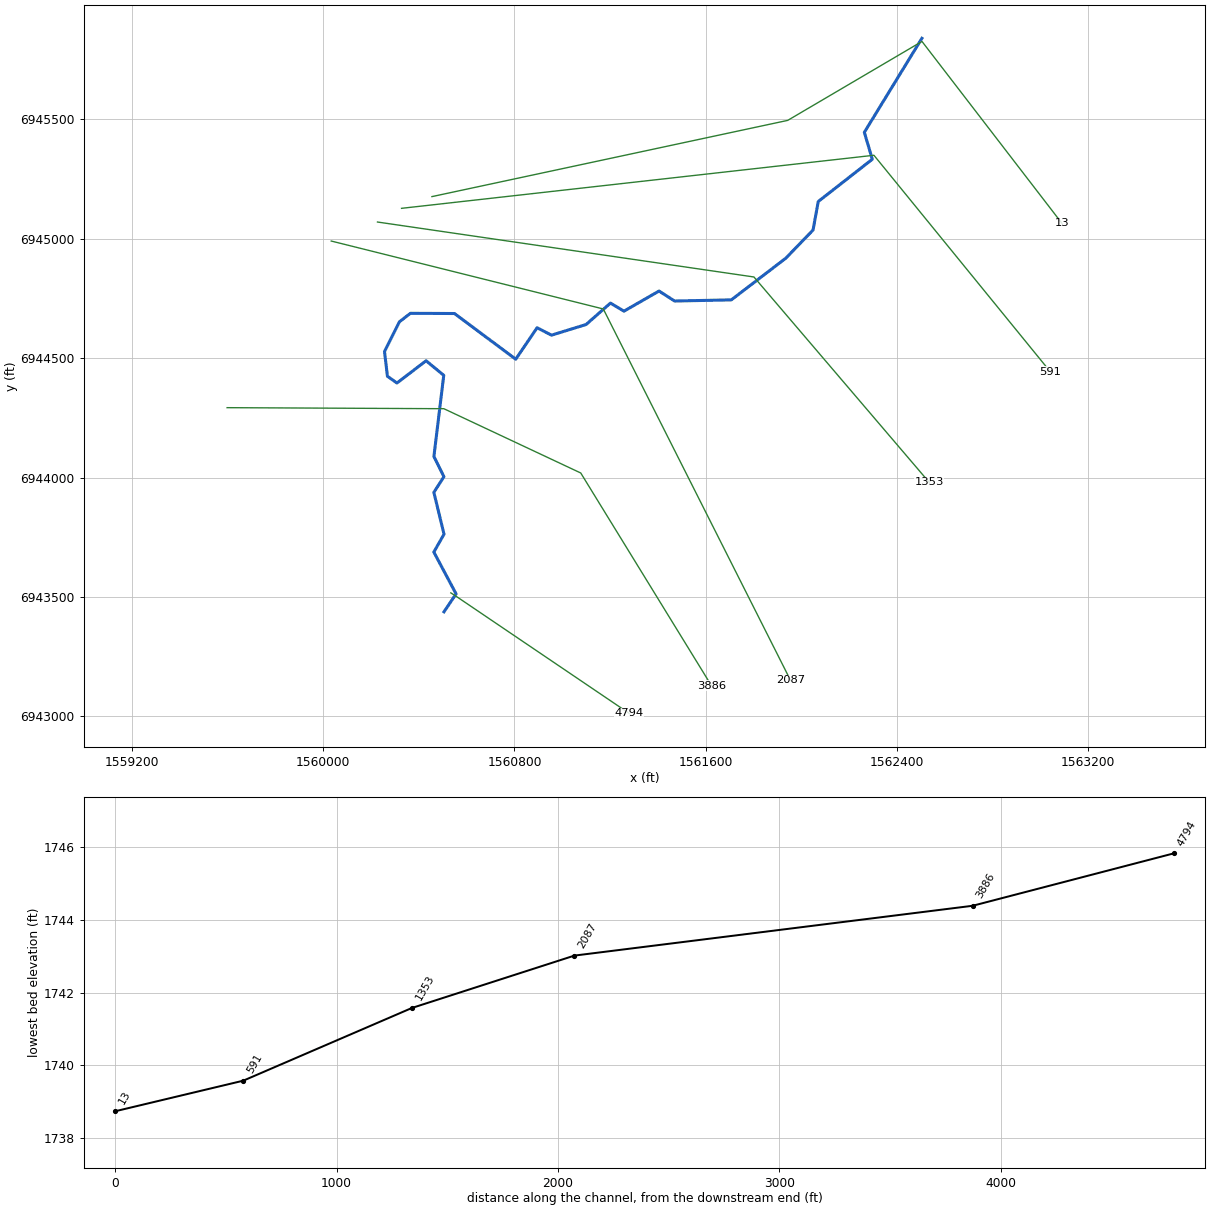
--- Chimney Creek 1111.prj (project) ---

Proj Title=Chimney Creek 1111 Base Level Engineering
Current Plan=p01
Default Exp/Contr=0.3,0.1
English Units
Geom File=g01
Flow File=f01
Plan File=p01
BEGIN DESCRIPTION:
Chimney Creek 1111
END DESCRIPTION:

--- Chimney Creek 1111.p01 (plan) ---

Plan Title=Multiple Run
Short Identifier=Multiple
Geom File=g01
Flow File=f01
Subcritical Flow
K Sum by GR= 0
Std Step Tol= 0.01
Critical Tol= 0.01
Num of Std Step Trials= 20
Max Error Tol= 0.3
Flow Tol Ratio= 0.001
Split Flow NTrial= 30
Split Flow Tol= 0.02
Split Flow Ratio= 0.02
Log Output Level= 0
Friction Slope Method= 1
Unsteady Friction Slope Method= 2
Unsteady Bridges Friction Slope Method= 1
Parabolic Critical Depth
Global Vel Dist=  1 , 1 , 1
Global Log Level= 0
CheckData=True
Encroach Param= -1, 0, 0, 0
BEGIN DESCRIPTION:
Multiple Run
END DESCRIPTION:

--- Chimney Creek 1111.f01 (steady flow) ---

Flow Title=Multiple
Number of Profiles=7
Profile Names=10-year,25-year,50-year,1pct_min,100-year,1pct_plu,500-year
River Rch & RM= Chimney Creek 11,Reach-1,4794
     185     244     291     172     343     685     485
River Rch & RM= Chimney Creek 11,Reach-1,13
     449     622     763     465     927    1849    1386
Boundary for River Rch & Prof#=Chimney Creek 11,Reach-1,1
Up Type=0
Dn Type=3
Dn Slope=0.005
Boundary for River Rch & Prof#=Chimney Creek 11,Reach-1,2
Up Type=0
Dn Type=3
Dn Slope=0.005
Boundary for River Rch & Prof#=Chimney Creek 11,Reach-1,3
Up Type=0
Dn Type=3
Dn Slope=0.005
Boundary for River Rch & Prof#=Chimney Creek 11,Reach-1,4
Up Type=0
Dn Type=3
Dn Slope=0.005
Boundary for River Rch & Prof#=Chimney Creek 11,Reach-1,5
Up Type=0
Dn Type=3
Dn Slope=0.005
Boundary for River Rch & Prof#=Chimney Creek 11,Reach-1,6
Up Type=0
Dn Type=3
Dn Slope=0.005
Boundary for River Rch & Prof#=Chimney Creek 11,Reach-1,7
Up Type=0
Dn Type=3
Dn Slope=0.005

--- Chimney Creek 1111.g01 (geometry) ---

Geom Title=Existing Conditions

River Reach=Chimney Creek 11,Reach-1
Reach XY= 30
      1560505.00      6943438.00      1560555.62      6943513.06
      1560462.53      6943687.99      1560505.13      6943762.89
      1560462.59      6943938.01      1560504.71      6944003.36
      1560462.81      6944088.09      1560504.02      6944427.76
      1560430.09      6944488.62      1560308.12      6944395.52
      1560268.34      6944423.85      1560256.08      6944527.45
      1560318.47      6944651.71      1560364.64      6944687.27
      1560548.95      6944686.34      1560805.30      6944495.20
      1560894.68      6944626.89      1560954.89      6944595.81
      1561099.52      6944640.28      1561201.67      6944729.99
      1561258.23      6944696.25      1561404.99      6944780.47
      1561470.16      6944738.66      1561707.45      6944743.46
      1561935.16      6944917.61      1562049.47      6945035.58
      1562071.30      6945155.13      1562297.50      6945331.95
      1562264.17      6945444.72      1562505.00      6945838.00

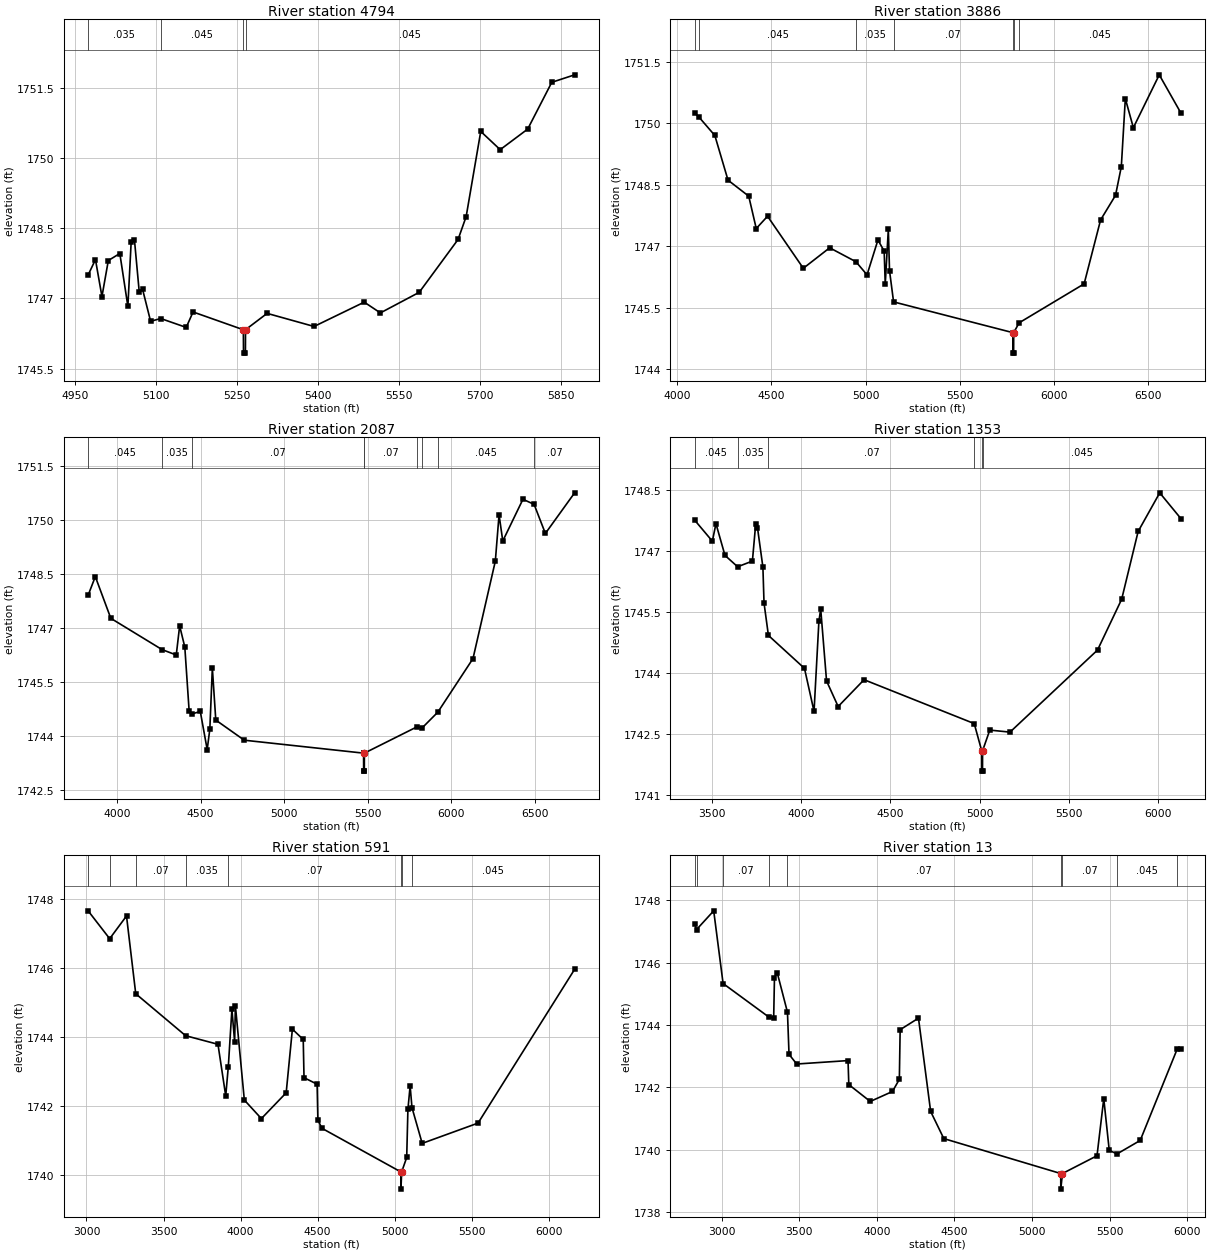
Type RM Length L Ch R = 1,4794,908,908,908
BEGIN DESCRIPTION:
Chimney Creek 1111 4.0
END DESCRIPTION:
XS GIS Cut Line= 3
      1560533.73      6943517.27      1560555.26      6943503.40
      1561280.02      6943012.98
#Sta/Elev= 30
  4974.4 1747.50  4988.0 1747.83  5000.0 1747.04  5011.8 1747.81  5033.1 1747.96
  5048.0 1746.83  5054.1 1748.21  5060.2 1748.25  5069.1 1747.13  5075.1 1747.20
  5090.1 1746.51  5108.8 1746.57  5156.0 1746.38  5168.7 1746.71  5261.8 1746.33
  5262.1 1745.83  5265.6 1745.83  5265.8 1746.33  5305.8 1746.68  5392.7 1746.40
  5485.6 1746.92  5515.5 1746.69  5587.4 1747.13  5659.3 1748.26  5674.3 1748.75
  5701.3 1750.57  5737.3 1750.18  5788.2 1750.62  5832.8 1751.62  5875.1 1751.78
#Mann=4,-1,0
  4974.4   0.035       0  5108.8   0.045       0  5261.8   0.035       0
  5265.8   0.045       0
Bank Sta=5261.8,5265.8
Exp/Cntr=0.3,0.1

Type RM Length L Ch R = 1,3886,1799,1799,1799
BEGIN DESCRIPTION:
Mapping XS 5b94d525
END DESCRIPTION:
XS GIS Cut Line= 4
      1559597.37      6944292.37      1560504.45      6944288.03
      1561077.36      6944018.93      1561624.22      6943129.20
#Sta/Elev= 30
  4091.9 1750.25  4116.8 1750.14  4199.5 1749.70  4269.5 1748.61  4379.5 1748.22
  4419.5 1747.43  4479.5 1747.73  4669.5 1746.46  4809.5 1746.96  4949.0 1746.62
  5008.0 1746.30  5065.9 1747.15  5099.0 1746.88  5104.7 1746.07  5121.1 1747.41
  5127.5 1746.40  5149.0 1745.64  5782.5 1744.89  5782.8 1744.39  5786.7 1744.39
  5787.1 1744.89  5816.1 1745.13  6161.2 1746.08  6248.7 1747.64  6328.0 1748.24
  6358.8 1748.94  6380.1 1750.60  6422.7 1749.89  6560.3 1751.18  6676.3 1750.24
#Mann=7,-1,0
  4091.9    0.16       0  4116.8   0.045       0  4949.0   0.035       0
  5149.0    0.07       0  5782.5   0.035       0  5787.1    0.07       0
  5816.1   0.045       0
Bank Sta=5782.5,5787.1
Exp/Cntr=0.3,0.1

Type RM Length L Ch R = 1,2087,734,734,734
BEGIN DESCRIPTION:
Chimney Creek 1111 3.0
END DESCRIPTION:
XS GIS Cut Line= 3
      1560033.16      6944989.72      1561171.71      6944705.42
      1561955.08      6943151.52
#Sta/Elev= 30
  3826.5 1747.91  3869.6 1748.43  3962.4 1747.27  4269.3 1746.40  4354.4 1746.25
  4374.7 1747.06  4405.6 1746.47  4431.7 1744.68  4448.4 1744.61  4498.3 1744.68
  4539.6 1743.62  4555.5 1744.19  4570.5 1745.89  4591.1 1744.44  4761.8 1743.88
  5476.3 1743.52  5476.7 1743.02  5480.7 1743.02  5481.0 1743.52  5795.3 1744.25
  5826.5 1744.22  5920.9 1744.66  6131.5 1746.15  6265.3 1748.86  6287.6 1750.15
  6309.9 1749.42  6430.6 1750.58  6497.5 1750.44  6565.0 1749.63  6740.2 1750.76
#Mann=9,-1,0
  3826.5   0.045       0  4269.3   0.035       0  4448.4    0.07       0
  5476.3    0.07       0  5481.0    0.07       0  5795.3   0.045       0
  5826.5    0.07       0  5920.9   0.045       0  6497.5    0.07       0
Bank Sta=5476.3,5481
Exp/Cntr=0.3,0.1

Type RM Length L Ch R = 1,1353,762,762,762
BEGIN DESCRIPTION:
Mapping XS 89a4431a
END DESCRIPTION:
XS GIS Cut Line= 3
      1560226.67      6945069.28      1561802.19      6944839.24
      1562535.71      6943979.85
#Sta/Elev= 30
  3405.1 1747.76  3504.5 1747.24  3524.7 1747.67  3575.2 1746.89  3645.9 1746.61
  3728.6 1746.75  3747.0 1747.66  3757.1 1747.57  3787.4 1746.60  3793.6 1745.72
  3818.2 1744.92  4019.9 1744.11  4073.5 1743.05  4100.7 1745.27  4110.8 1745.57
  4143.5 1743.80  4208.4 1743.17  4353.4 1743.83  4969.8 1742.75  5011.6 1742.08
  5012.0 1741.58  5016.1 1741.58  5016.4 1742.08  5056.8 1742.59  5169.9 1742.54
  5659.6 1744.56  5794.7 1745.81  5886.9 1747.48  6007.7 1748.43  6127.2 1747.79
#Mann=6,-1,0
  3405.1   0.045       0  3645.9   0.035       0  3818.2    0.07       0
  4969.8   0.045       0  5011.6   0.045       0  5016.4   0.045       0
Bank Sta=5011.6,5016.4
Exp/Cntr=0.3,0.1

Type RM Length L Ch R = 1,591,578,578,578
BEGIN DESCRIPTION:
Chimney Creek 1111 2.0
END DESCRIPTION:
XS GIS Cut Line= 3
      1560327.39      6945126.57      1562304.35      6945348.64
      1563042.45      6944442.77
#Sta/Elev= 30
  3010.6 1747.67  3150.6 1746.86  3259.8 1747.52  3319.7 1745.26  3643.5 1744.04
  3853.5 1743.79  3903.8 1742.29  3920.6 1743.14  3944.0 1744.81  3961.6 1743.86
  3966.6 1744.91  4024.6 1742.17  4135.2 1741.63  4296.2 1742.38  4336.5 1744.23
  4406.9 1743.93  4412.0 1742.82  4497.0 1742.63  4502.0 1741.59  4527.7 1741.35
  5040.8 1740.08  5041.2 1739.58  5045.7 1740.08  5078.5 1740.50  5086.4 1741.90
  5100.7 1742.58  5112.8 1741.95  5179.0 1740.91  5541.7 1741.50  6168.5 1745.97
#Mann=8,-1,0
  3010.6   0.045       0  3150.6   0.035       0  3319.7    0.07       0
  3643.5   0.035       0  3920.6    0.07       0  5040.8    0.07       0
  5045.7    0.07       0  5112.8   0.045       0
Bank Sta=5040.8,5045.7
Exp/Cntr=0.3,0.1

Type RM Length L Ch R = 1,13,0,0,0
BEGIN DESCRIPTION:
Chimney Creek 1111 1.0
END DESCRIPTION:
XS GIS Cut Line= 4
      1560454.55      6945175.62      1561943.46      6945494.62
      1562505.42      6945825.02      1563090.75      6945064.23
#Sta/Elev= 30
  2825.4 1747.25  2838.1 1747.06  2948.6 1747.66  3009.1 1745.33  3302.5 1744.26
  3335.0 1744.23  3340.1 1745.52  3357.7 1745.68  3423.8 1744.41  3433.9 1743.06
  3483.3 1742.75  3814.0 1742.86  3819.1 1742.09  3957.2 1741.55  4100.4 1741.87
  4144.7 1742.26  4149.8 1743.85  4267.9 1744.22  4346.3 1741.23  4431.1 1740.36
  5184.4 1739.24  5184.9 1738.74  5195.3 1739.24  5418.2 1739.81  5461.7 1741.64
  5497.1 1739.98  5547.7 1739.87  5696.4 1740.30  5934.0 1743.22  5959.9 1743.22
#Mann=9,-1,0
  2825.4   0.045       0  2838.1   0.035       0  3009.1    0.07       0
  3302.5   0.035       0  3423.8    0.07       0  5184.4    0.07       0
  5195.3    0.07       0  5547.7   0.045       0  5934.0   0.035       0
Bank Sta=5184.4,5195.3
Exp/Cntr=0.3,0.1

Chan Stop Cuts=-1