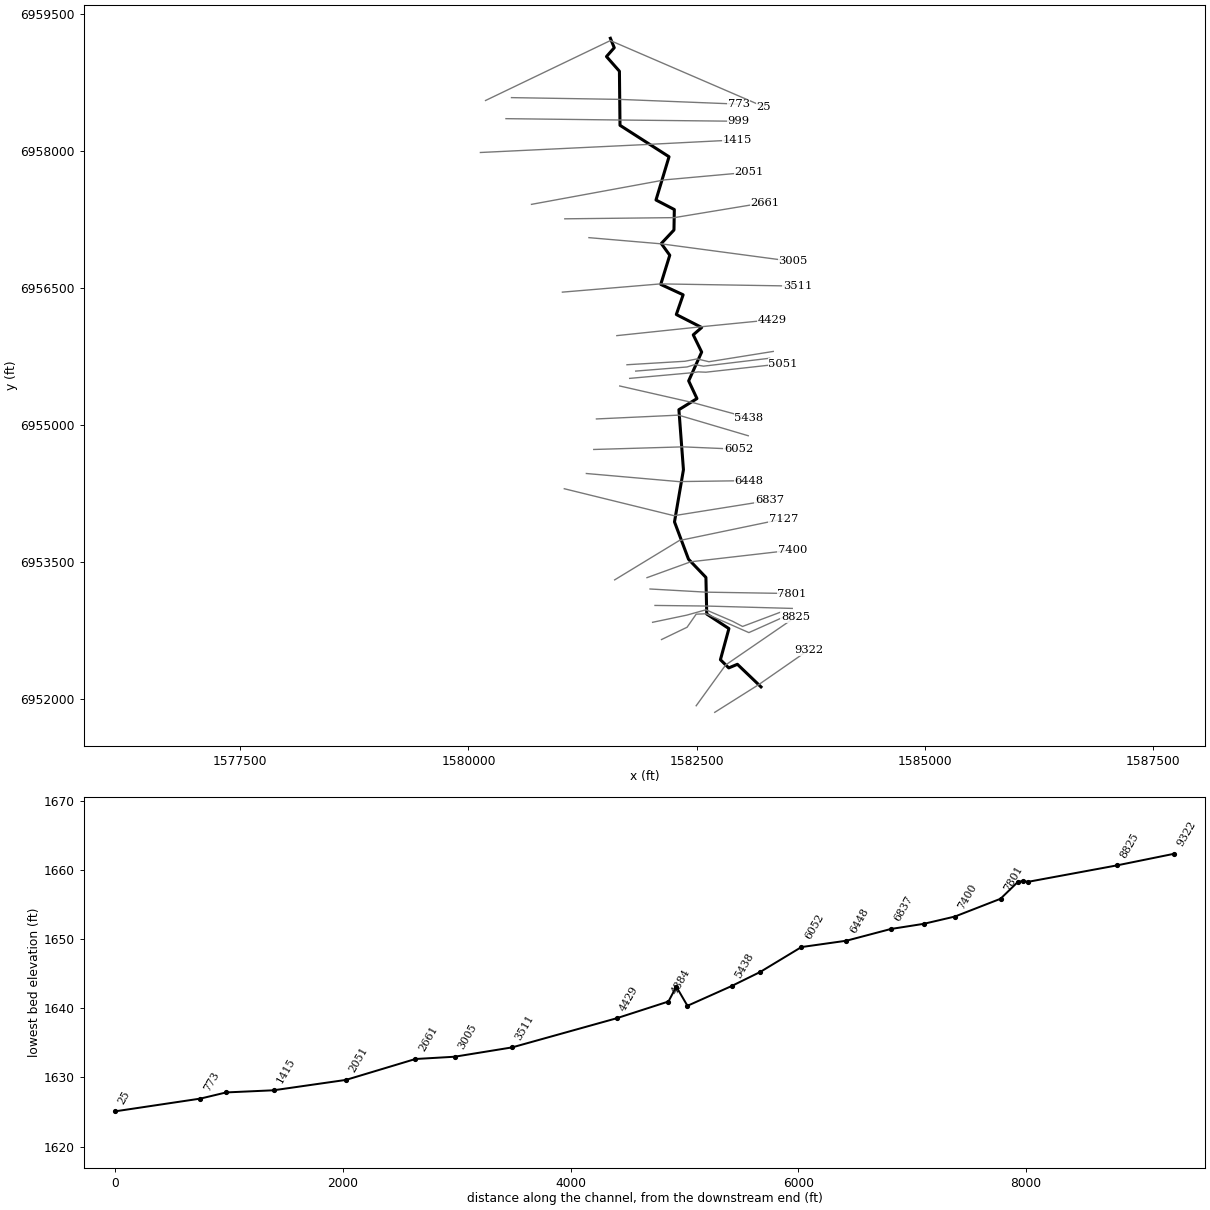
--- Chimney Creek 1112.prj (project) ---

Proj Title=Chimney Creek 1112 Base Level Engineering
Current Plan=p01
Default Exp/Contr=0.3,0.1
English Units
Geom File=g01
Flow File=f01
Plan File=p01
BEGIN DESCRIPTION:
Chimney Creek 1112
END DESCRIPTION:

--- Chimney Creek 1112.p01 (plan) ---

Plan Title=Multiple Run
Short Identifier=Multiple
Geom File=g01
Flow File=f01
Subcritical Flow
K Sum by GR= 0
Std Step Tol= 0.01
Critical Tol= 0.01
Num of Std Step Trials= 20
Max Error Tol= 0.3
Flow Tol Ratio= 0.001
Split Flow NTrial= 30
Split Flow Tol= 0.02
Split Flow Ratio= 0.02
Log Output Level= 0
Friction Slope Method= 1
Unsteady Friction Slope Method= 2
Unsteady Bridges Friction Slope Method= 1
Parabolic Critical Depth
Global Vel Dist=  1 , 1 , 1
Global Log Level= 0
CheckData=True
Encroach Param= -1, 0, 0, 0
BEGIN DESCRIPTION:
Multiple Run
END DESCRIPTION:

--- Chimney Creek 1112.f01 (steady flow) ---

Flow Title=Multiple
Number of Profiles=7
Profile Names=10-year,25-year,50-year,1pct_min,100-year,1pct_plu,500-year
River Rch & RM= Chimney Creek 11,Reach-1,9322
     290     406     503     310     619    1234     948
River Rch & RM= Chimney Creek 11,Reach-1,8043
     420     598     749     467     931    1857    1457
River Rch & RM= Chimney Creek 11,Reach-1,5438
     469     670     842     526    1049    2092    1650
River Rch & RM= Chimney Creek 11,Reach-1,4429
     582     839    1060     665    1327    2647    2107
River Rch & RM= Chimney Creek 11,Reach-1,999
     615     887    1121     704    1404    2801    2231
Boundary for River Rch & Prof#=Chimney Creek 11,Reach-1,1
Up Type=0
Dn Type=3
Dn Slope=0.005
Boundary for River Rch & Prof#=Chimney Creek 11,Reach-1,2
Up Type=0
Dn Type=3
Dn Slope=0.005
Boundary for River Rch & Prof#=Chimney Creek 11,Reach-1,3
Up Type=0
Dn Type=3
Dn Slope=0.005
Boundary for River Rch & Prof#=Chimney Creek 11,Reach-1,4
Up Type=0
Dn Type=3
Dn Slope=0.005
Boundary for River Rch & Prof#=Chimney Creek 11,Reach-1,5
Up Type=0
Dn Type=3
Dn Slope=0.005
Boundary for River Rch & Prof#=Chimney Creek 11,Reach-1,6
Up Type=0
Dn Type=3
Dn Slope=0.005
Boundary for River Rch & Prof#=Chimney Creek 11,Reach-1,7
Up Type=0
Dn Type=3
Dn Slope=0.005

--- Chimney Creek 1112.g01 (geometry) ---

Geom Title=Existing Conditions

River Reach=Chimney Creek 11,Reach-1
Reach XY= 30
      1583205.00      6952138.00      1582946.50      6952385.33
      1582851.60      6952345.82      1582760.37      6952435.60
      1582853.38      6952776.19      1582610.45      6952935.53
      1582601.46      6953336.54      1582410.83      6953535.70
      1582257.26      6953943.94      1582355.28      6954515.16
      1582305.54      6955172.41      1582503.39      6955294.03
      1582412.53      6955487.99      1582554.93      6955803.39
      1582462.71      6955991.64      1582555.24      6956072.30
      1582277.16      6956214.22      1582352.10      6956430.07
      1582106.56      6956543.86      1582205.49      6956863.04
      1582112.60      6956991.34      1582251.46      6957139.46
      1582255.42      6957363.42      1582054.50      6957467.76
      1582197.41      6957941.35      1581660.36      6958285.30
      1581653.95      6958877.57      1581512.09      6959038.00
      1581597.38      6959134.61      1581555.00      6959238.00

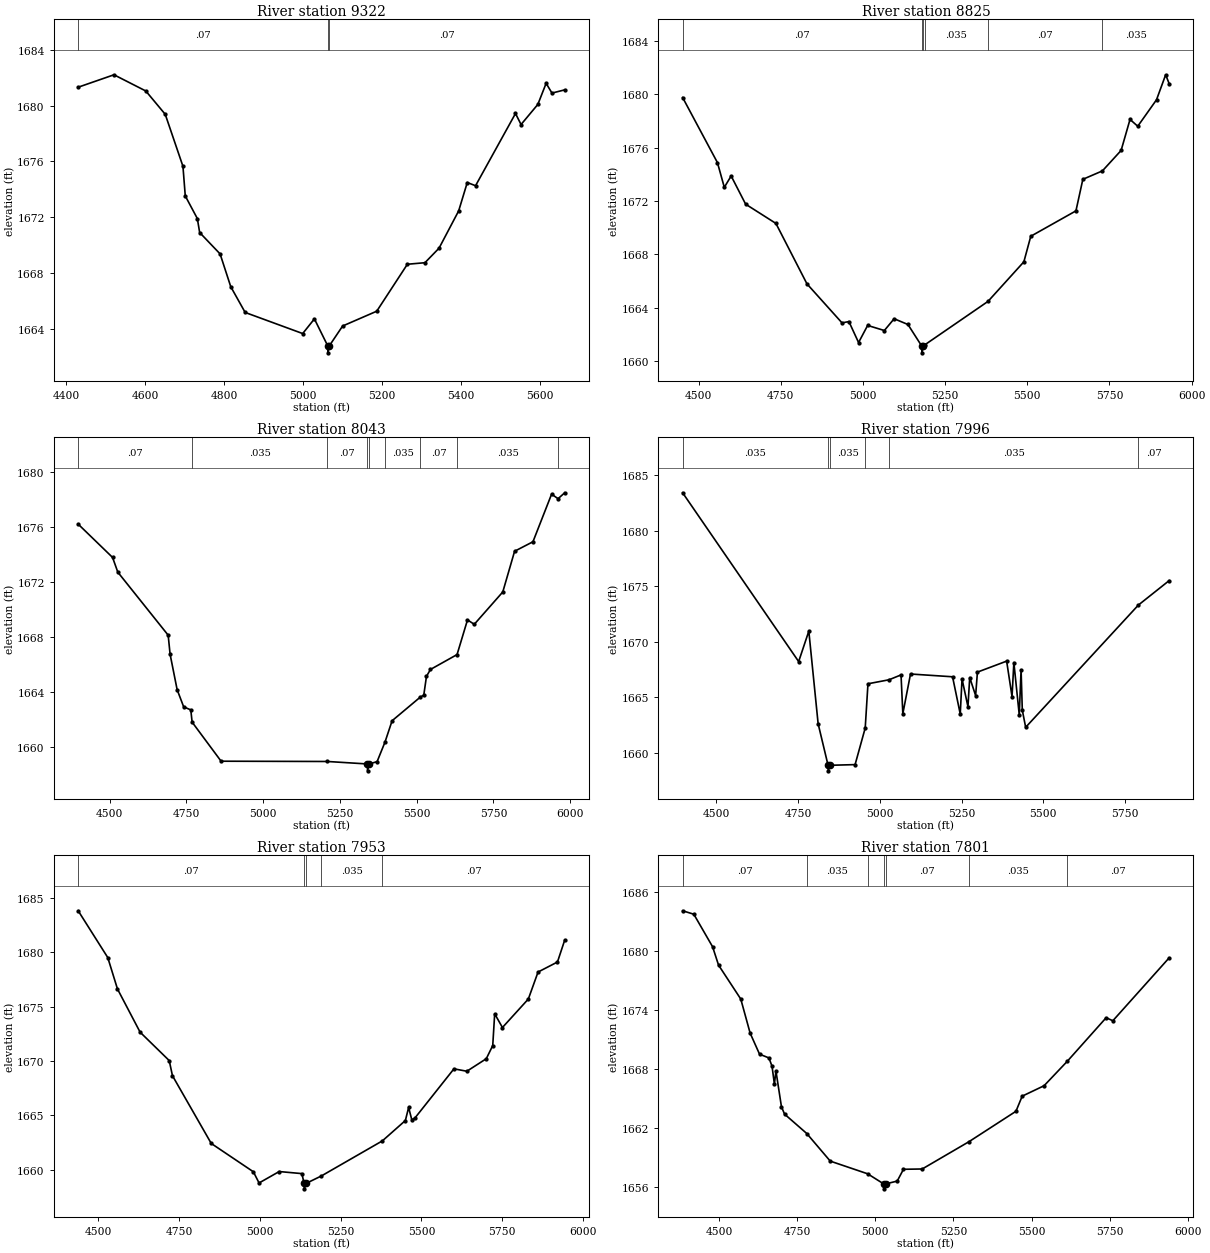
Type RM Length L Ch R = 1,9322,497,497,497
BEGIN DESCRIPTION:
Chimney Creek 1112 19.0
END DESCRIPTION:
XS GIS Cut Line= 3
      1582698.18      6951859.52      1583180.00      6952163.00
      1583725.93      6952541.79
#Sta/Elev= 30
  4430.0 1681.31  4520.8 1682.20  4601.5 1681.04  4650.8 1679.37  4695.7 1675.65
  4701.6 1673.53  4732.2 1671.91  4738.1 1670.91  4789.9 1669.38  4817.0 1667.03
  4853.5 1665.19  4999.4 1663.68  5029.1 1664.73  5062.9 1662.80  5063.2 1662.30
  5066.9 1662.80  5100.7 1664.22  5187.2 1665.28  5264.9 1668.64  5309.4 1668.75
  5345.2 1669.79  5395.0 1672.46  5416.8 1674.49  5437.8 1674.26  5539.1 1679.43
  5553.2 1678.64  5595.8 1680.08  5616.8 1681.59  5631.6 1680.89  5663.9 1681.12
#Mann=3,-1,0
  4430.0    0.07       0  5062.9    0.07       0  5066.9    0.07       0
Bank Sta=5062.9,5066.9
Exp/Cntr=0.3,0.1

Type RM Length L Ch R = 1,8825,782,782,782
BEGIN DESCRIPTION:
Mapping XS d6992f09
END DESCRIPTION:
XS GIS Cut Line= 3
      1582494.85      6951931.47      1582818.23      6952378.56
      1583583.73      6952903.35
#Sta/Elev= 30
  4451.6 1679.74  4557.5 1674.87  4578.4 1673.02  4599.2 1673.87  4643.3 1671.76
  4735.4 1670.32  4829.8 1665.80  4936.5 1662.88  4957.4 1662.98  4986.8 1661.41
  5014.4 1662.69  5065.2 1662.31  5095.0 1663.19  5137.0 1662.76  5179.1 1661.14
  5179.4 1660.64  5183.5 1661.14  5188.3 1661.24  5380.6 1664.49  5489.6 1667.45
  5510.6 1669.36  5648.0 1671.26  5669.0 1673.62  5728.5 1674.25  5785.4 1675.78
  5812.5 1678.10  5836.0 1677.59  5893.1 1679.57  5920.9 1681.44  5931.5 1680.78
#Mann=6,-1,0
  4451.6    0.07       0  5179.1    0.07       0  5183.5    0.07       0
  5188.3   0.035       0  5380.6    0.07       0  5728.5   0.035       0
Bank Sta=5179.1,5183.5
Exp/Cntr=0.3,0.1

Type RM Length L Ch R = 1,8043,47,47,47
BEGIN DESCRIPTION:
Mapping XS dcc8ed36
END DESCRIPTION:
XS GIS Cut Line= 6
      1582115.14      6952656.35      1582395.05      6952790.88
      1582494.88      6952934.11      1582603.38      6952938.45
      1583072.13      6952732.29      1583503.99      6952925.43
#Sta/Elev= 30
  4397.5 1676.19  4509.5 1673.77  4526.6 1672.70  4690.6 1668.12  4696.9 1666.73
  4719.8 1664.16  4741.1 1662.91  4764.3 1662.69  4768.6 1661.80  4863.0 1658.96
  5209.3 1658.94  5339.4 1658.76  5339.9 1658.26  5345.5 1658.76  5371.1 1658.93
  5396.8 1660.35  5419.9 1661.90  5511.8 1663.62  5523.1 1663.76  5531.9 1665.13
  5545.0 1665.63  5631.5 1666.71  5665.5 1669.23  5687.6 1668.91  5780.4 1671.26
  5818.9 1674.22  5878.7 1674.91  5939.4 1678.37  5960.5 1678.04  5982.1 1678.47
#Mann=9,-1,0
  4397.5    0.07       0  4768.6   0.035       0  5209.3    0.07       0
  5339.4   0.035       0  5345.5    0.07       0  5396.8   0.035       0
  5511.8    0.07       0  5631.5   0.035       0  5960.5    0.07       0
Bank Sta=5339.4,5345.5
Exp/Cntr=0.3,0.1

Type RM Length L Ch R = 1,7996,43,43,43
BEGIN DESCRIPTION:
Mapping XS 859f05a3
END DESCRIPTION:
XS GIS Cut Line= 6
      1582017.41      6952845.13      1582390.71      6952923.26
      1582601.21      6952981.85      1582894.18      6952855.99
      1583002.69      6952799.56      1583421.84      6952957.29
#Sta/Elev= 30
  4396.5 1683.43  4751.6 1668.23  4782.7 1670.97  4811.2 1662.63  4841.6 1658.89
  4842.1 1658.39  4847.7 1658.89  4924.3 1658.95  4955.3 1662.25  4963.7 1666.23
  5028.1 1666.59  5064.9 1667.03  5070.4 1663.54  5093.9 1667.11  5222.6 1666.86
  5246.1 1663.51  5251.6 1666.66  5269.7 1664.17  5275.1 1666.79  5293.2 1665.17
  5298.7 1667.28  5388.1 1668.27  5404.6 1665.08  5410.2 1668.14  5426.7 1663.43
  5432.3 1667.50  5436.0 1663.86  5446.3 1662.31  5791.3 1673.32  5885.4 1675.52
#Mann=6,-1,0
  4396.5   0.035       0  4841.6    0.07       0  4847.7   0.035       0
  4955.3    0.07       0  5028.1   0.035       0  5791.3    0.07       0
Bank Sta=4841.6,4847.7
Exp/Cntr=0.3,0.1

Type RM Length L Ch R = 1,7953,152,152,152
BEGIN DESCRIPTION:
Mapping XS 80ea8542
END DESCRIPTION:
XS GIS Cut Line= 3
      1582043.48      6953029.60      1582605.55      6953023.09
      1583547.38      6952997.05
#Sta/Elev= 30
  4438.6 1683.80  4530.1 1679.50  4560.1 1676.61  4630.1 1672.64  4720.1 1670.03
  4730.1 1668.64  4850.1 1662.41  4980.2 1659.81  4997.9 1658.78  5060.2 1659.83
  5130.2 1659.64  5137.2 1658.74  5137.7 1658.24  5143.3 1658.74  5190.9 1659.43
  5379.2 1662.65  5450.3 1664.52  5460.3 1665.72  5470.3 1664.57  5480.3 1664.77
  5600.4 1669.27  5640.4 1669.05  5700.4 1670.20  5720.4 1671.41  5726.4 1674.33
  5750.4 1673.07  5830.5 1675.69  5860.5 1678.17  5920.5 1679.09  5942.9 1681.10
#Mann=5,-1,0
  4438.6    0.07       0  5137.2    0.07       0  5143.3    0.07       0
  5190.9   0.035       0  5379.2    0.07       0
Bank Sta=5137.2,5143.3
Exp/Cntr=0.3,0.1

Type RM Length L Ch R = 1,7801,401,401,401
BEGIN DESCRIPTION:
Mapping XS 8c6dcd1a
END DESCRIPTION:
XS GIS Cut Line= 3
      1581989.21      6953209.72      1582603.38      6953175.00
      1583545.21      6953159.81
#Sta/Elev= 30
  4383.2 1684.10  4419.0 1683.75  4479.1 1680.44  4498.2 1678.57  4569.3 1675.12
  4599.3 1671.65  4629.4 1669.51  4659.4 1669.13  4669.4 1668.28  4676.9 1666.47
  4681.9 1667.80  4699.5 1664.16  4709.5 1663.41  4780.5 1661.44  4855.7 1658.63
  4975.4 1657.34  5026.9 1656.31  5027.4 1655.81  5033.0 1656.31  5070.0 1656.60
  5090.0 1657.80  5150.0 1657.83  5299.3 1660.60  5450.0 1663.70  5470.0 1665.24
  5540.0 1666.30  5614.4 1668.79  5738.7 1673.22  5760.1 1672.91  5940.3 1679.31
#Mann=7,-1,0
  4383.2    0.07       0  4780.5   0.035       0  4975.4    0.07       0
  5026.9    0.07       0  5033.0    0.07       0  5299.3   0.035       0
  5614.4    0.07       0
Bank Sta=5026.9,5033
Exp/Cntr=0.3,0.1

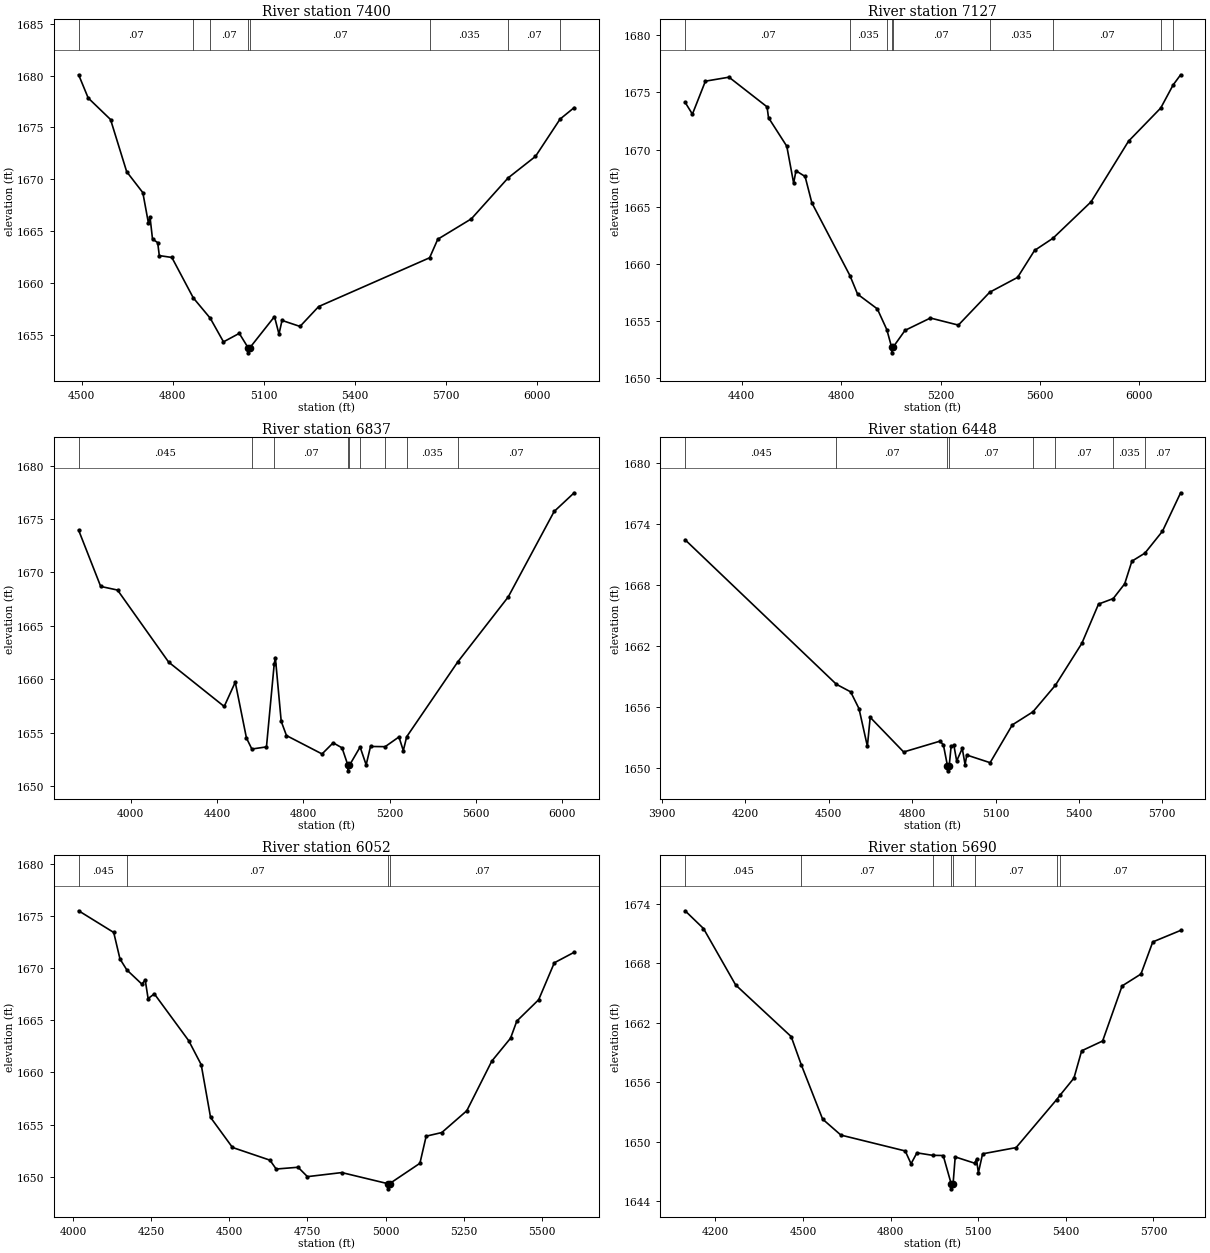
Type RM Length L Ch R = 1,7400,273,273,273
BEGIN DESCRIPTION:
Mapping XS b8b9c301
END DESCRIPTION:
XS GIS Cut Line= 3
      1581956.08      6953333.84      1582435.21      6953507.43
      1583551.66      6953635.72
#Sta/Elev= 30
  4490.5 1680.09  4522.0 1677.85  4595.7 1675.77  4648.9 1670.73  4702.1 1668.71
  4720.5 1665.78  4725.8 1666.36  4734.0 1664.23  4751.1 1663.88  4756.4 1662.63
  4797.8 1662.45  4868.4 1658.55  4924.4 1656.58  4968.0 1654.30  5020.0 1655.12
  5049.0 1653.74  5049.5 1653.24  5055.1 1653.74  5136.1 1656.74  5150.9 1655.05
  5160.9 1656.37  5220.2 1655.79  5281.7 1657.71  5647.4 1662.42  5674.3 1664.21
  5785.0 1666.18  5906.1 1670.13  5996.4 1672.21  6077.4 1675.81  6123.9 1676.92
#Mann=8,-1,0
  4490.5    0.07       0  4868.4   0.035       0  4924.4    0.07       0
  5049.0    0.07       0  5055.1    0.07       0  5647.4   0.035       0
  5906.1    0.07       0  6077.4   0.035       0
Bank Sta=5049,5055.1
Exp/Cntr=0.3,0.1

Type RM Length L Ch R = 1,7127,290,290,290
BEGIN DESCRIPTION:
Mapping XS ab1a25b5
END DESCRIPTION:
XS GIS Cut Line= 3
      1581601.89      6953309.52      1582308.76      6953739.56
      1583450.36      6953976.83
#Sta/Elev= 30
  4172.6 1674.14  4202.0 1673.10  4254.3 1675.99  4349.2 1676.34  4502.3 1673.74
  4508.1 1672.79  4581.7 1670.29  4609.3 1667.05  4618.5 1668.14  4655.3 1667.64
  4682.5 1665.33  4835.6 1658.96  4866.5 1657.33  4945.9 1656.04  4984.1 1654.22
  5003.3 1652.69  5003.8 1652.19  5009.4 1652.69  5057.4 1654.16  5159.4 1655.24
  5271.9 1654.62  5398.0 1657.50  5510.1 1658.80  5578.3 1661.16  5652.5 1662.23
  5805.7 1665.42  5956.3 1670.73  6086.0 1673.64  6135.8 1675.66  6166.0 1676.55
#Mann=9,-1,0
  4172.6    0.07       0  4835.6   0.035       0  4984.1    0.07       0
  5003.3    0.07       0  5009.4    0.07       0  5398.0   0.035       0
  5652.5    0.07       0  6086.0   0.035       0  6135.8    0.07       0
Bank Sta=5003.3,5009.4
Exp/Cntr=0.3,0.1

Type RM Length L Ch R = 1,6837,389,389,389
BEGIN DESCRIPTION:
Mapping XS 80cf280e
END DESCRIPTION:
XS GIS Cut Line= 3
      1581050.03      6954307.20      1582251.42      6954012.06
      1583296.60      6954178.74
#Sta/Elev= 30
  3759.5 1673.95  3861.7 1668.69  3939.7 1668.35  4176.5 1661.61  4433.9 1657.46
  4485.0 1659.73  4536.9 1654.51  4561.9 1653.48  4629.6 1653.68  4665.5 1661.44
  4670.8 1662.04  4697.9 1656.07  4722.3 1654.74  4887.0 1653.02  4938.5 1654.06
  4979.7 1653.59  5007.3 1651.94  5007.8 1651.44  5013.5 1651.94  5063.4 1653.67
  5091.4 1652.00  5111.6 1653.72  5179.4 1653.70  5243.3 1654.61  5263.5 1653.33
  5279.2 1654.63  5516.1 1661.64  5749.6 1667.71  5962.2 1675.70  6055.0 1677.45
#Mann=9,-1,0
  3759.5   0.045       0  4561.9   0.035       0  4665.5    0.07       0
  5007.3    0.07       0  5013.5    0.07       0  5063.4    0.16       0
  5179.4    0.07       0  5279.2   0.035       0  5516.1    0.07       0
Bank Sta=5007.3,5013.5
Exp/Cntr=0.3,0.1

Type RM Length L Ch R = 1,6448,396,396,396
BEGIN DESCRIPTION:
Mapping XS 9dbe5e65
END DESCRIPTION:
XS GIS Cut Line= 3
      1581291.89      6954473.87      1582302.28      6954385.33
      1583070.25      6954395.74
#Sta/Elev= 30
  3983.4 1672.42  4527.6 1658.24  4578.8 1657.50  4608.9 1655.85  4639.0 1652.16
  4649.1 1655.00  4769.5 1651.60  4900.0 1652.66  4912.4 1652.30  4927.0 1650.25
  4927.5 1649.75  4933.3 1650.25  4940.2 1652.16  4950.2 1652.24  4960.2 1650.72
  4980.3 1651.95  4990.4 1650.35  4996.5 1651.30  5080.4 1650.55  5160.4 1654.26
  5234.5 1655.54  5315.6 1658.16  5410.4 1662.26  5470.4 1666.11  5523.2 1666.65
  5564.5 1668.10  5590.4 1670.32  5637.3 1671.11  5700.4 1673.26  5765.7 1677.03
#Mann=8,-1,0
  3983.4   0.045       0  4527.6    0.07       0  4927.0    0.07       0
  4933.3    0.07       0  5234.5   0.035       0  5315.6    0.07       0
  5523.2   0.035       0  5637.3    0.07       0
Bank Sta=4927,4933.3
Exp/Cntr=0.3,0.1

Type RM Length L Ch R = 1,6052,362,362,362
BEGIN DESCRIPTION:
Mapping XS 7daa06d0
END DESCRIPTION:
XS GIS Cut Line= 3
      1581372.64      6954736.89      1582351.76      6954765.53
      1582958.56      6954739.49
#Sta/Elev= 30
  4017.2 1675.50  4129.6 1673.42  4149.6 1670.88  4171.5 1669.83  4219.6 1668.47
  4230.4 1668.86  4239.7 1667.08  4259.7 1667.53  4369.7 1663.04  4409.7 1660.74
  4439.7 1655.68  4509.8 1652.80  4629.8 1651.58  4649.8 1650.73  4719.9 1650.90
  4749.9 1650.00  4859.9 1650.39  5006.8 1649.33  5007.3 1648.83  5013.1 1649.33
  5110.1 1651.28  5130.1 1653.88  5180.2 1654.23  5260.2 1656.32  5340.3 1661.08
  5400.4 1663.28  5420.4 1664.92  5490.4 1666.97  5540.5 1670.51  5604.1 1671.52
#Mann=4,-1,0
  4017.2   0.045       0  4171.5    0.07       0  5006.8    0.07       0
  5013.1    0.07       0
Bank Sta=5006.8,5013.1
Exp/Cntr=0.3,0.1

Type RM Length L Ch R = 1,5690,252,252,252
BEGIN DESCRIPTION:
Mapping XS 3884ccaf
END DESCRIPTION:
XS GIS Cut Line= 3
      1581402.10      6955071.09      1582301.42      6955112.76
      1583065.29      6954887.07
#Sta/Elev= 30
  4096.5 1673.27  4159.5 1671.48  4269.6 1665.79  4459.8 1660.58  4494.2 1657.75
  4567.4 1652.26  4630.0 1650.65  4850.2 1649.05  4870.2 1647.76  4890.3 1648.86
  4943.8 1648.61  4980.3 1648.59  5007.7 1645.73  5008.2 1645.23  5014.1 1645.73
  5021.4 1648.45  5087.5 1647.82  5094.4 1648.19  5100.7 1646.85  5115.2 1648.76
  5229.9 1649.39  5368.8 1654.23  5380.9 1654.69  5428.0 1656.40  5454.4 1659.15
  5526.2 1660.14  5592.8 1665.69  5657.4 1666.89  5697.9 1670.13  5793.3 1671.29
#Mann=8,-1,0
  4096.5   0.045       0  4494.2    0.07       0  4943.8    0.16       0
  5007.7    0.07       0  5014.1    0.16       0  5087.5    0.07       0
  5368.8   0.035       0  5380.9    0.07       0
Bank Sta=5007.7,5014.1
Exp/Cntr=0.3,0.1

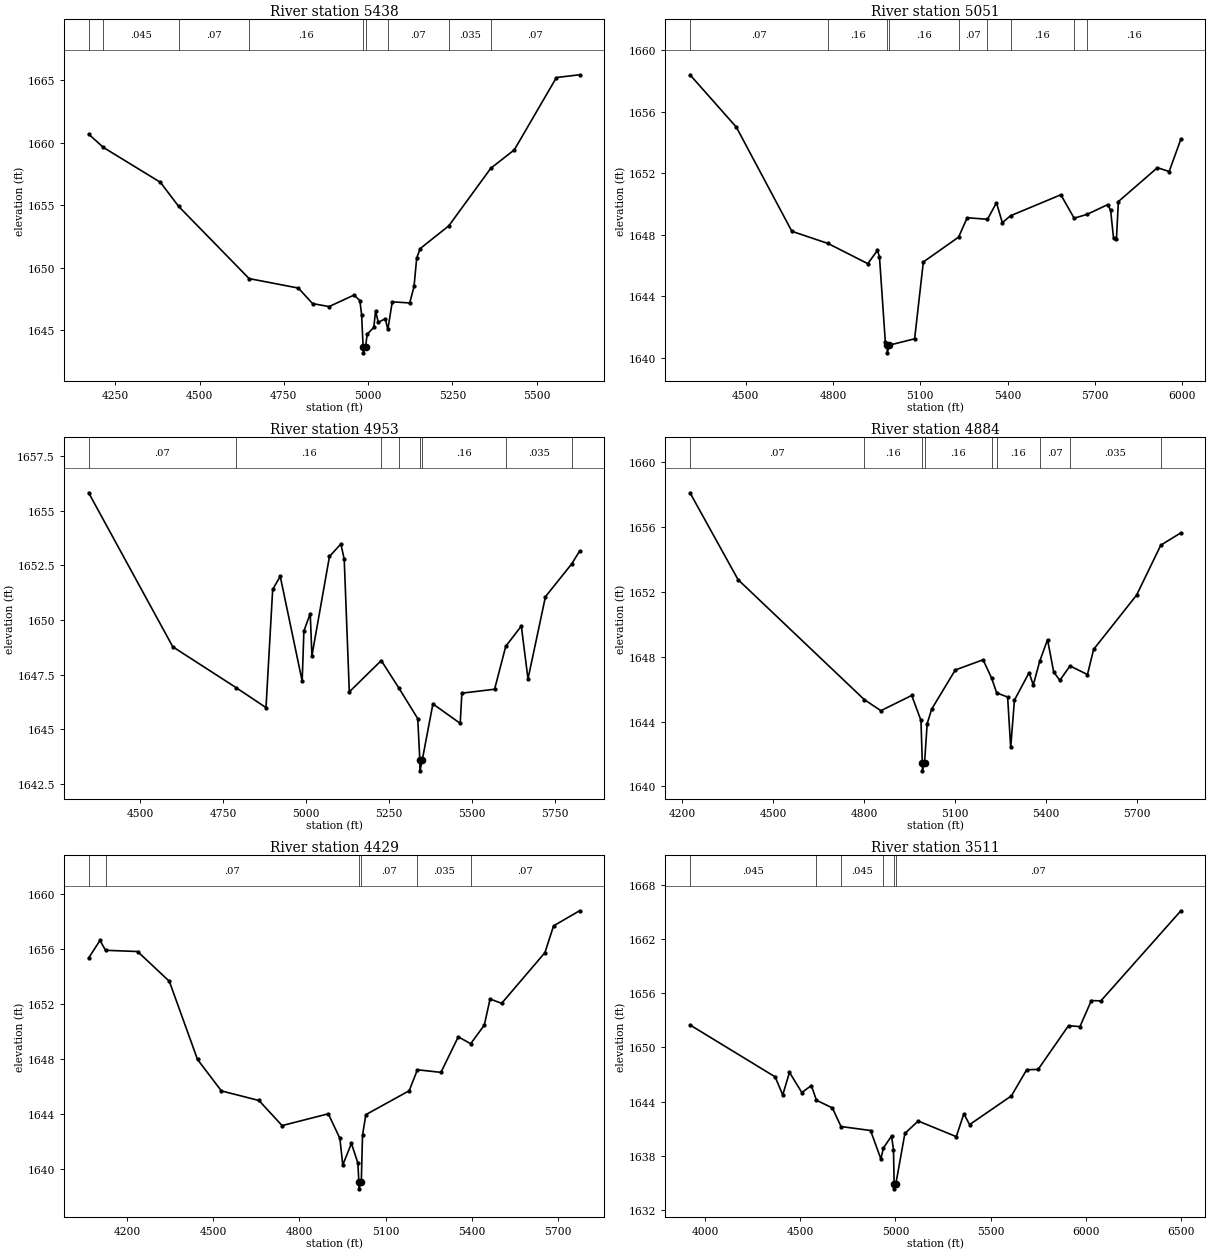
Type RM Length L Ch R = 1,5438,387,387,387
BEGIN DESCRIPTION:
Mapping XS ea51bedf
END DESCRIPTION:
XS GIS Cut Line= 3
      1581657.36      6955431.93      1582466.41      6955247.90
      1583071.09      6955083.30
#Sta/Elev= 30
  4170.9 1660.68  4214.6 1659.62  4383.8 1656.83  4438.0 1654.90  4646.9 1649.13
  4793.1 1648.37  4835.1 1647.13  4884.3 1646.89  4958.1 1647.81  4975.6 1647.37
  4980.7 1646.25  4985.2 1643.69  4985.7 1643.19  4992.6 1643.69  4997.3 1644.68
  5017.0 1645.23  5022.2 1646.55  5030.2 1645.63  5051.0 1645.92  5058.6 1645.06
  5071.7 1647.27  5123.5 1647.18  5136.3 1648.50  5144.2 1650.78  5154.6 1651.53
  5239.5 1653.35  5364.2 1657.96  5433.7 1659.42  5558.8 1665.21  5627.3 1665.43
#Mann=9,-1,0
  4170.9   0.035       0  4214.6   0.045       0  4438.0    0.07       0
  4646.9    0.16       0  4985.2    0.07       0  4992.6    0.16       0
  5058.6    0.07       0  5239.5   0.035       0  5364.2    0.07       0
Bank Sta=4985.2,4992.6
Exp/Cntr=0.3,0.1

Type RM Length L Ch R = 1,5051,98,98,98
BEGIN DESCRIPTION:
Mapping XS 86787896
END DESCRIPTION:
XS GIS Cut Line= 5
      1581766.26      6955515.09      1582457.21      6955577.58
      1582516.24      6955586.26      1582601.31      6955582.79
      1583445.04      6955676.54
#Sta/Elev= 30
  4308.4 1658.39  4467.8 1654.99  4658.6 1648.23  4782.8 1647.44  4919.6 1646.13
  4953.0 1646.99  4959.8 1646.56  4979.9 1641.05  4986.2 1640.84  4986.7 1640.34
  4993.6 1640.84  5080.6 1641.25  5110.6 1646.24  5231.7 1647.85  5261.4 1649.11
  5331.0 1649.01  5362.0 1650.08  5382.1 1648.79  5410.4 1649.24  5583.3 1650.60
  5629.0 1649.08  5673.6 1649.33  5744.3 1649.96  5754.4 1649.59  5764.4 1647.79
  5774.5 1647.76  5781.1 1650.16  5915.4 1652.36  5955.6 1652.11  5995.9 1654.21
#Mann=9,-1,0
  4308.4    0.07       0  4782.8    0.16       0  4986.2    0.07       0
  4993.6    0.16       0  5231.7    0.07       0  5331.0   0.035       0
  5410.4    0.16       0  5629.0   0.035       0  5673.6    0.16       0
Bank Sta=4986.2,4993.6
Exp/Cntr=0.3,0.1

Type RM Length L Ch R = 1,4953,69,69,69
BEGIN DESCRIPTION:
Mapping XS 5cb18d83
END DESCRIPTION:
XS GIS Cut Line= 5
      1581832.19      6955594.94      1582394.71      6955640.08
      1582481.52      6955666.12      1582575.27      6955648.76
      1583299.18      6955735.56
#Sta/Elev= 30
  4343.9 1655.82  4597.5 1648.78  4788.6 1646.91  4878.4 1646.00  4898.5 1651.40
  4921.3 1652.00  4987.4 1647.21  4992.6 1649.50  5011.7 1650.30  5016.8 1648.37
  5069.7 1652.91  5104.0 1653.48  5114.1 1652.79  5129.5 1646.72  5225.8 1648.15
  5278.2 1646.91  5335.7 1645.50  5342.0 1643.61  5342.5 1643.11  5349.4 1643.61
  5381.4 1646.17  5463.7 1645.28  5468.7 1646.66  5567.3 1646.84  5600.9 1648.80
  5647.9 1649.73  5668.0 1647.31  5720.6 1651.07  5799.7 1652.57  5823.3 1653.15
#Mann=8,-1,0
  4343.9    0.07       0  4788.6    0.16       0  5225.8   0.035       0
  5278.2    0.16       0  5342.0    0.07       0  5349.4    0.16       0
  5600.9   0.035       0  5799.7    0.07       0
Bank Sta=5342,5349.4
Exp/Cntr=0.3,0.1

Type RM Length L Ch R = 1,4884,455,455,455
BEGIN DESCRIPTION:
Mapping XS d28c7b69
END DESCRIPTION:
XS GIS Cut Line= 5
      1581736.72      6955664.39      1582372.14      6955702.58
      1582505.82      6955728.62      1582634.29      6955697.37
      1583339.13      6955810.22
#Sta/Elev= 30
  4226.1 1658.11  4384.7 1652.75  4800.5 1645.36  4855.5 1644.67  4957.3 1645.61
  4987.8 1644.07  4992.2 1641.46  4992.7 1640.96  4999.6 1641.46  5008.3 1643.87
  5023.2 1644.77  5100.9 1647.18  5192.6 1647.81  5221.0 1646.67  5237.5 1645.77
  5273.6 1645.51  5283.7 1642.40  5296.0 1645.32  5344.5 1647.02  5358.1 1646.25
  5379.4 1647.72  5405.2 1649.05  5425.5 1647.06  5445.7 1646.54  5479.3 1647.43
  5536.9 1646.90  5557.1 1648.45  5698.9 1651.80  5778.8 1654.88  5844.9 1655.64
#Mann=9,-1,0
  4226.1    0.07       0  4800.5    0.16       0  4992.2    0.07       0
  4999.6    0.16       0  5221.0   0.035       0  5237.5    0.16       0
  5379.4    0.07       0  5479.3   0.035       0  5778.8    0.07       0
Bank Sta=4992.2,4999.6
Exp/Cntr=0.3,0.1

Type RM Length L Ch R = 1,4429,918,918,918
BEGIN DESCRIPTION:
Mapping XS 9f082d7a
END DESCRIPTION:
XS GIS Cut Line= 3
      1581625.68      6955983.14      1582554.46      6956080.79
      1583324.83      6956156.75
#Sta/Elev= 30
  4066.8 1655.37  4106.3 1656.65  4125.5 1655.93  4237.0 1655.84  4347.5 1653.67
  4445.6 1647.97  4528.6 1645.68  4659.4 1644.98  4739.9 1643.15  4900.7 1644.01
  4940.9 1642.22  4951.0 1640.28  4981.1 1641.85  5003.5 1640.43  5007.0 1639.04
  5007.5 1638.54  5015.5 1639.04  5019.7 1642.45  5031.4 1643.95  5182.1 1645.69
  5210.7 1647.22  5292.6 1647.03  5352.9 1649.62  5396.0 1649.12  5443.4 1650.47
  5463.5 1652.38  5503.7 1652.06  5654.4 1655.76  5684.5 1657.71  5774.8 1658.81
#Mann=6,-1,0
  4066.8   0.045       0  4125.5    0.07       0  5007.0    0.07       0
  5015.5    0.07       0  5210.7   0.035       0  5396.0    0.07       0
Bank Sta=5007,5015.5
Exp/Cntr=0.3,0.1

Type RM Length L Ch R = 1,3511,506,506,506
BEGIN DESCRIPTION:
Mapping XS 44ec2817
END DESCRIPTION:
XS GIS Cut Line= 3
      1581029.09      6956459.26      1582105.50      6956549.54
      1583605.51      6956525.24
#Sta/Elev= 30
  3919.9 1652.48  4367.4 1646.73  4407.5 1644.73  4442.9 1647.23  4507.9 1644.99
  4557.9 1645.77  4584.6 1644.14  4668.4 1643.29  4713.8 1641.23  4869.1 1640.79
  4923.1 1637.65  4937.1 1638.87  4979.5 1640.18  4989.6 1638.65  4993.1 1634.83
  4993.6 1634.33  5001.6 1634.83  5049.6 1640.47  5119.6 1641.84  5319.6 1640.11
  5359.6 1642.64  5389.6 1641.44  5609.7 1644.63  5689.7 1647.52  5749.7 1647.55
  5909.7 1652.40  5969.7 1652.29  6029.7 1655.18  6079.7 1655.14  6500.3 1665.12
#Mann=6,-1,0
  3919.9   0.045       0  4584.6    0.07       0  4713.8   0.045       0
  4937.1    0.07       0  4993.1    0.07       0  5001.6    0.07       0
Bank Sta=4993.1,5001.6
Exp/Cntr=0.3,0.1

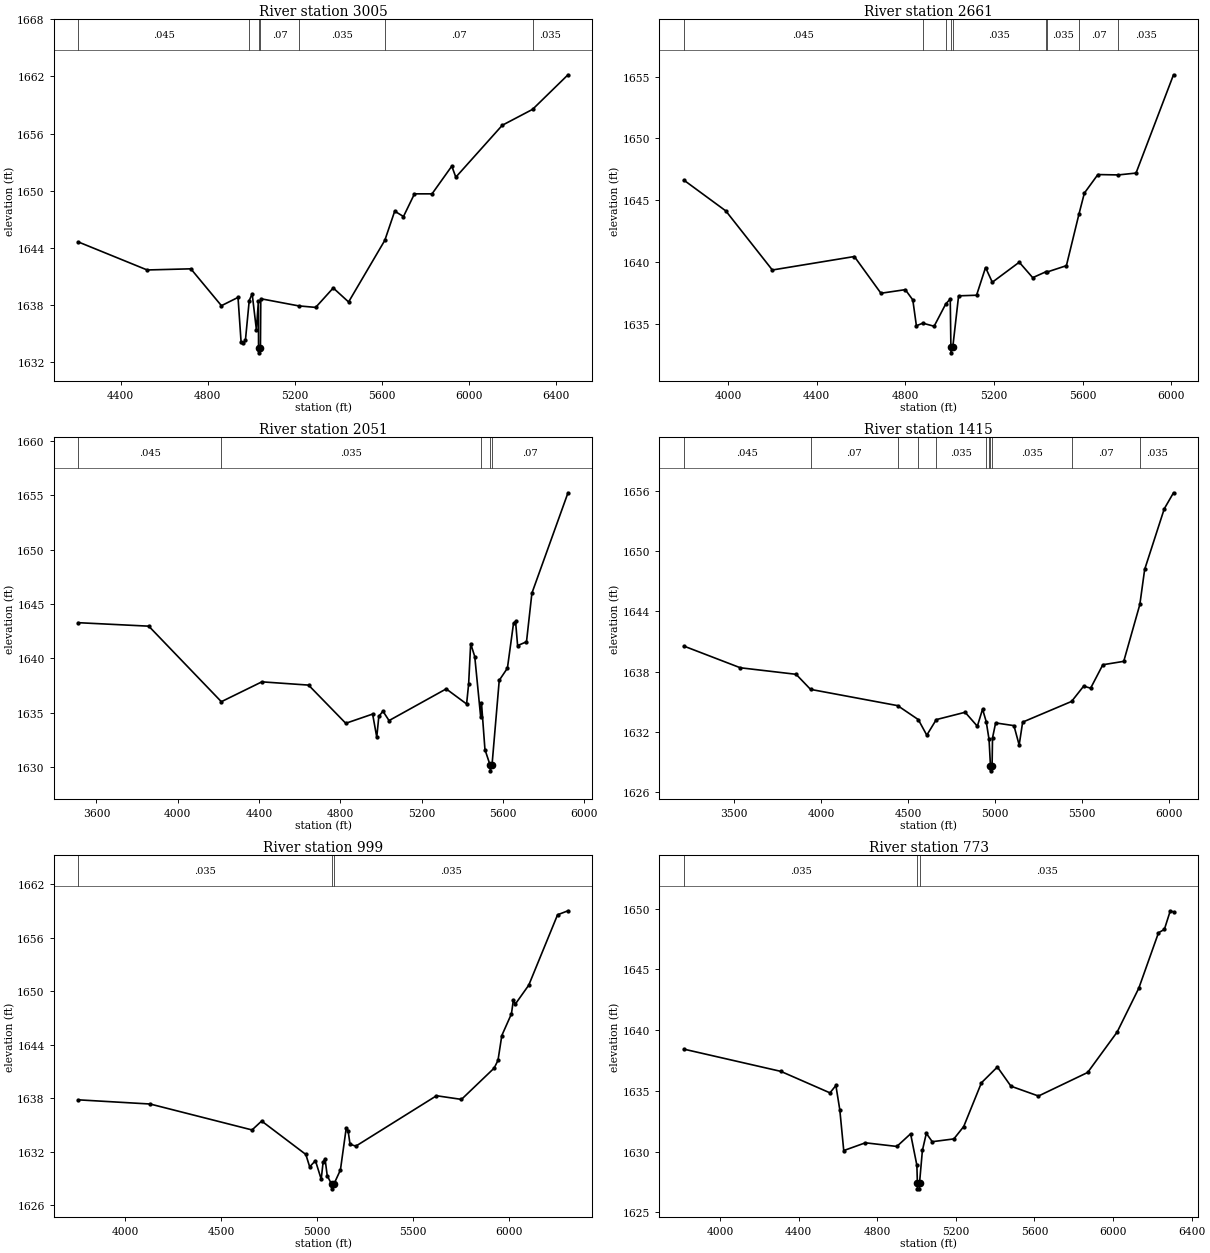
Type RM Length L Ch R = 1,3005,344,344,344
BEGIN DESCRIPTION:
Mapping XS 7468e956
END DESCRIPTION:
XS GIS Cut Line= 3
      1581319.90      6957055.62      1582111.58      6956987.91
      1583554.30      6956795.20
#Sta/Elev= 30
  4204.9 1644.62  4521.1 1641.68  4721.9 1641.80  4862.4 1637.93  4938.7 1638.80
  4952.7 1634.13  4962.8 1634.02  4972.8 1634.33  4990.2 1638.47  5003.7 1639.18
  5023.1 1635.41  5032.4 1638.45  5033.0 1633.48  5033.5 1632.98  5041.7 1633.48
  5043.3 1638.66  5217.1 1637.91  5295.5 1637.75  5376.2 1639.79  5446.8 1638.32
  5613.2 1644.79  5658.7 1647.85  5699.0 1647.29  5749.5 1649.67  5830.2 1649.67
  5921.0 1652.58  5939.5 1651.42  6153.0 1656.87  6292.2 1658.54  6455.0 1662.17
#Mann=7,-1,0
  4204.9   0.045       0  4990.2    0.07       0  5033.0    0.07       0
  5041.7    0.07       0  5217.1   0.035       0  5613.2    0.07       0
  6292.2   0.035       0
Bank Sta=5033,5041.7
Exp/Cntr=0.3,0.1

Type RM Length L Ch R = 1,2661,610,610,610
BEGIN DESCRIPTION:
Mapping XS 2e037060
END DESCRIPTION:
XS GIS Cut Line= 3
      1581055.58      6957261.80      1582255.64      6957274.82
      1583251.91      6957439.42
#Sta/Elev= 30
  3800.4 1646.62  3989.8 1644.13  4199.8 1639.35  4569.9 1640.44  4689.9 1637.47
  4799.9 1637.76  4833.7 1636.93  4849.9 1634.84  4878.8 1635.05  4929.9 1634.80
  4982.3 1636.60  5002.7 1637.01  5005.6 1633.15  5006.1 1632.65  5014.4 1633.15
  5040.4 1637.26  5121.5 1637.31  5162.0 1639.55  5192.5 1638.36  5314.1 1639.98
  5374.9 1638.73  5434.7 1639.21  5438.6 1639.18  5526.9 1639.70  5584.0 1643.90
  5608.0 1645.57  5669.0 1647.07  5761.0 1647.04  5841.1 1647.19  6010.3 1655.14
#Mann=9,-1,0
  3800.4   0.045       0  4878.8    0.07       0  4982.3   0.035       0
  5005.6   0.035       0  5014.4   0.035       0  5434.7    0.07       0
  5438.6   0.035       0  5584.0    0.07       0  5761.0   0.035       0
Bank Sta=5005.6,5014.4
Exp/Cntr=0.3,0.1

Type RM Length L Ch R = 1,2051,636,636,636
BEGIN DESCRIPTION:
Mapping XS 452284a0
END DESCRIPTION:
XS GIS Cut Line= 3
      1580690.88      6957420.11      1582151.86      6957688.35
      1583071.91      6957771.52
#Sta/Elev= 30
  3511.0 1643.28  3857.5 1642.96  4214.6 1636.00  4414.0 1637.83  4643.7 1637.53
  4826.8 1634.01  4958.9 1634.86  4979.3 1632.73  4989.4 1634.64  5009.6 1635.13
  5039.7 1634.26  5320.9 1637.18  5421.3 1635.79  5431.3 1637.62  5441.3 1641.35
  5461.4 1640.16  5490.6 1634.59  5494.5 1635.90  5511.6 1631.59  5537.4 1630.13
  5537.9 1629.63  5546.2 1630.13  5581.9 1637.97  5622.1 1639.09  5652.2 1643.23
  5662.2 1643.39  5672.3 1641.17  5716.0 1641.52  5742.6 1646.00  5920.2 1655.25
#Mann=5,-1,0
  3511.0   0.045       0  4214.6   0.035       0  5490.6    0.07       0
  5537.4   0.035       0  5546.2    0.07       0
Bank Sta=5537.4,5546.2
Exp/Cntr=0.3,0.1

Type RM Length L Ch R = 1,1415,416,416,416
BEGIN DESCRIPTION:
Mapping XS 0bc9ab1c
END DESCRIPTION:
XS GIS Cut Line= 3
      1580130.98      6957987.82      1581920.09      6958073.76
      1582940.49      6958125.82
#Sta/Elev= 30
  3210.9 1640.55  3535.3 1638.39  3855.7 1637.74  3938.7 1636.24  4439.3 1634.62
  4557.8 1633.23  4606.5 1631.68  4661.0 1633.23  4826.8 1633.96  4896.9 1632.57
  4926.9 1634.27  4947.9 1633.03  4964.2 1631.25  4972.3 1628.63  4972.8 1628.13
  4981.6 1628.63  4984.1 1631.41  5002.0 1632.90  5107.1 1632.63  5137.2 1630.70
  5157.2 1632.98  5438.3 1635.04  5507.6 1636.56  5547.7 1636.36  5617.8 1638.69
  5737.9 1639.03  5830.4 1644.69  5858.1 1648.18  5970.8 1654.22  6023.8 1655.81
#Mann=11,-1,0
  3210.9   0.045       0  3938.7    0.07       0  4439.3   0.035       0
  4557.8    0.07       0  4661.0   0.035       0  4947.9    0.07       0
  4964.2   0.035       0  4972.3   0.035       0  4981.6   0.035       0
  5438.3    0.07       0  5830.4   0.035       0
Bank Sta=4972.3,4981.6
Exp/Cntr=0.3,0.1

Type RM Length L Ch R = 1,999,226,226,226
BEGIN DESCRIPTION:
Mapping XS 25e36283
END DESCRIPTION:
XS GIS Cut Line= 3
      1580411.10      6958358.16      1581650.29      6958343.56
      1582959.34      6958329.67
#Sta/Elev= 30
  3756.4 1637.81  4130.3 1637.34  4660.4 1634.43  4710.4 1635.43  4940.4 1631.68
  4960.4 1630.29  4990.4 1630.98  5020.4 1628.90  5030.4 1630.84  5040.4 1631.19
  5051.7 1629.30  5074.9 1628.32  5075.4 1627.82  5085.9 1628.32  5120.4 1629.94
  5150.4 1634.61  5160.4 1634.33  5170.4 1632.83  5200.4 1632.61  5620.4 1638.27
  5750.4 1637.86  5920.4 1641.37  5940.4 1642.24  5960.4 1645.03  6010.4 1647.46
  6020.4 1649.00  6030.4 1648.55  6100.5 1650.68  6250.5 1658.58  6304.8 1659.03
#Mann=3,-1,0
  3756.4   0.035       0  5074.9   0.035       0  5085.9   0.035       0
Bank Sta=5074.9,5085.9
Exp/Cntr=0.3,0.1

Type RM Length L Ch R = 1,773,748,748,748
BEGIN DESCRIPTION:
Mapping XS dc61d1e7
END DESCRIPTION:
XS GIS Cut Line= 3
      1580471.66      6958588.44      1581653.77      6958569.25
      1582961.37      6958517.22
#Sta/Elev= 30
  3816.5 1638.43  4309.9 1636.60  4559.9 1634.83  4589.9 1635.44  4609.9 1633.43
  4629.9 1630.08  4740.0 1630.72  4900.0 1630.42  4970.0 1631.46  5001.9 1628.87
  5004.5 1627.43  5005.0 1626.93  5015.0 1626.93  5015.5 1627.43  5030.0 1630.09
  5050.0 1631.50  5080.1 1630.81  5190.1 1631.04  5240.2 1632.06  5330.3 1635.66
  5411.4 1636.96  5480.4 1635.38  5620.5 1634.57  5870.7 1636.51  6020.8 1639.84
  6130.9 1643.45  6231.0 1648.01  6261.0 1648.29  6291.0 1649.82  6307.4 1649.72
#Mann=3,-1,0
  3816.5   0.035       0  5004.5   0.035       0  5015.5   0.035       0
Bank Sta=5004.5,5015.5
Exp/Cntr=0.3,0.1

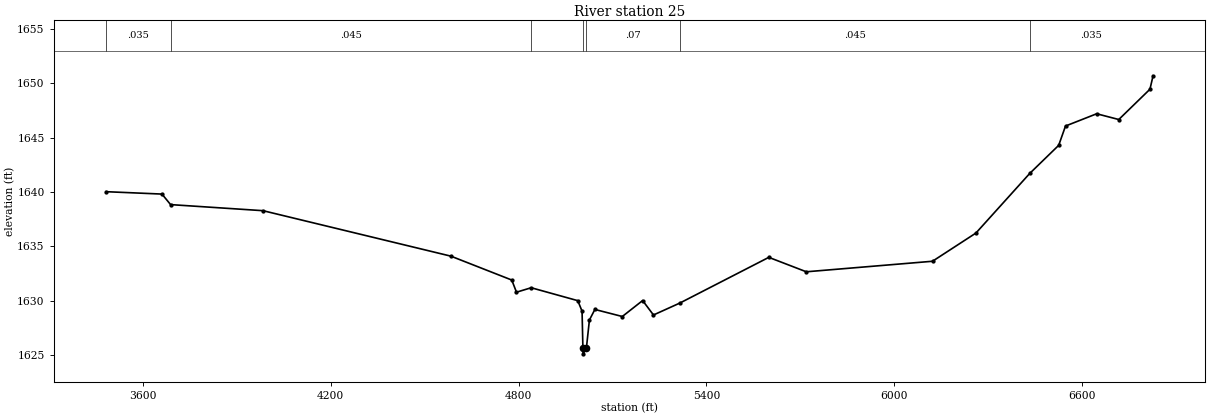
Type RM Length L Ch R = 1,25,0,0,0
BEGIN DESCRIPTION:
Chimney Creek 1112 1.0
END DESCRIPTION:
XS GIS Cut Line= 3
      1580187.39      6958556.95      1581554.86      6959213.00
      1583231.81      6958490.17
#Sta/Elev= 30
  3483.3 1640.03  3661.4 1639.81  3688.9 1638.84  3984.0 1638.28  4584.0 1634.09
  4778.3 1631.89  4793.4 1630.77  4840.4 1631.18  4989.1 1629.99  5002.8 1629.02
  5005.5 1625.59  5006.0 1625.09  5016.5 1625.59  5026.3 1628.21  5043.7 1629.18
  5131.3 1628.53  5196.2 1630.00  5230.8 1628.67  5315.1 1629.77  5599.1 1633.98
  5718.9 1632.65  6121.8 1633.62  6260.5 1636.22  6432.2 1641.71  6524.7 1644.30
  6546.5 1646.08  6646.0 1647.21  6716.6 1646.68  6816.1 1649.47  6826.1 1650.71
#Mann=7,-1,0
  3483.3   0.035       0  3688.9   0.045       0  4840.4    0.07       0
  5005.5    0.07       0  5016.5    0.07       0  5315.1   0.045       0
  6432.2   0.035       0
Bank Sta=5005.5,5016.5
Exp/Cntr=0.3,0.1

Chan Stop Cuts=-1