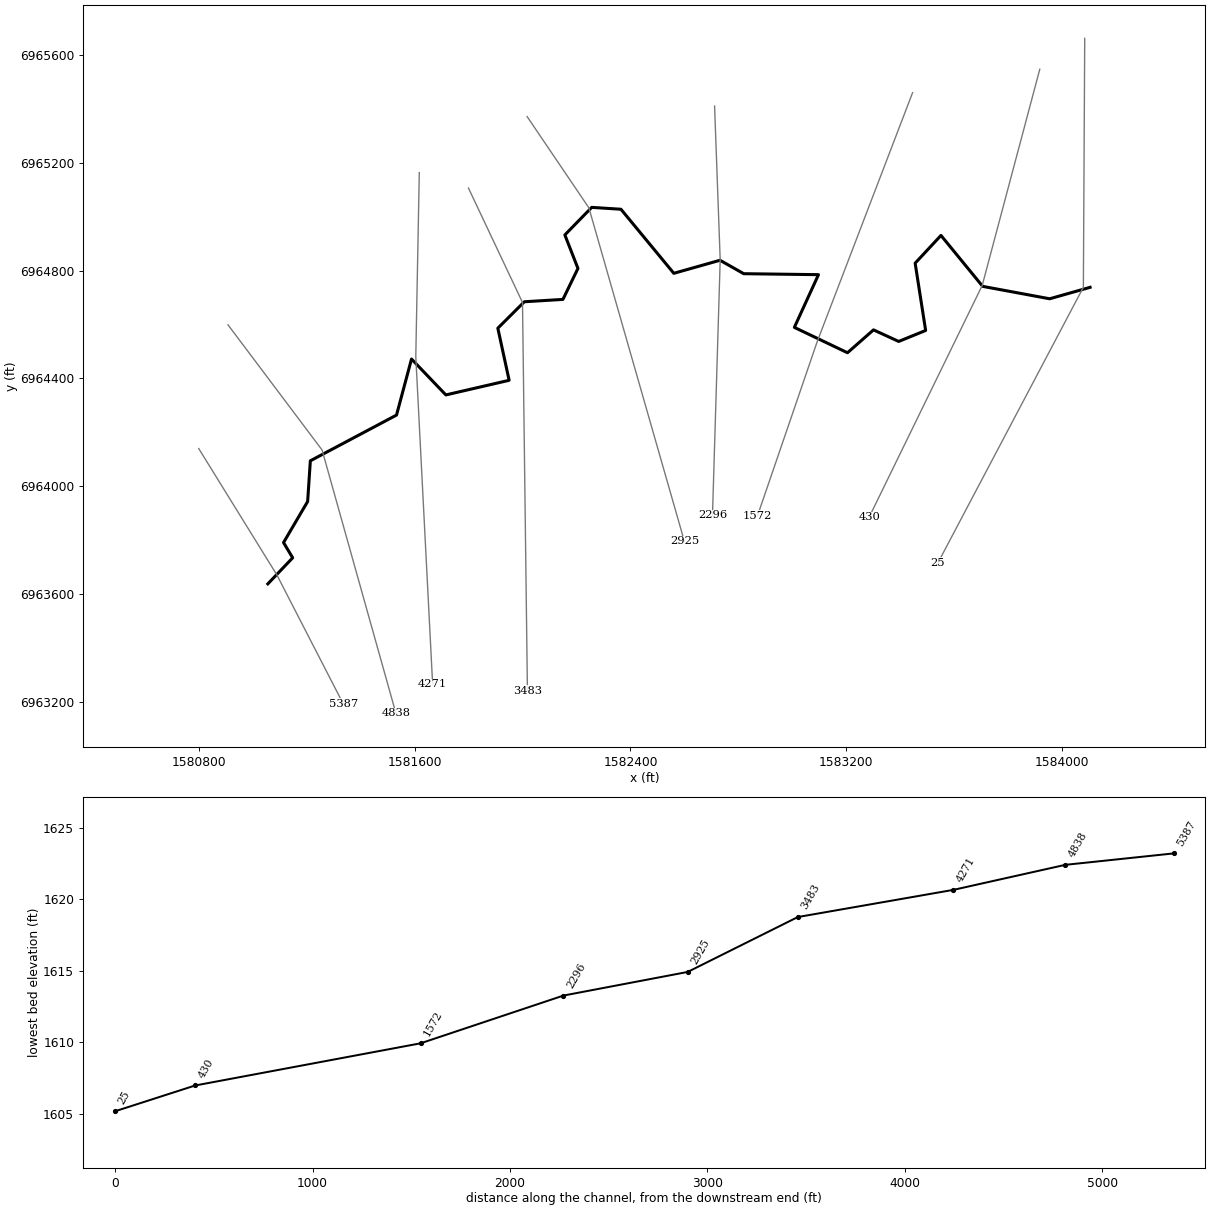
--- Chimney Creek 1113.prj (project) ---

Proj Title=Chimney Creek 1113 Base Level Engineering
Current Plan=p01
Default Exp/Contr=0.3,0.1
English Units
Geom File=g01
Flow File=f01
Plan File=p01
BEGIN DESCRIPTION:
Chimney Creek 1113
END DESCRIPTION:

--- Chimney Creek 1113.p01 (plan) ---

Plan Title=Multiple Run
Short Identifier=Multiple
Geom File=g01
Flow File=f01
Subcritical Flow
K Sum by GR= 0
Std Step Tol= 0.01
Critical Tol= 0.01
Num of Std Step Trials= 20
Max Error Tol= 0.3
Flow Tol Ratio= 0.001
Split Flow NTrial= 30
Split Flow Tol= 0.02
Split Flow Ratio= 0.02
Log Output Level= 0
Friction Slope Method= 1
Unsteady Friction Slope Method= 2
Unsteady Bridges Friction Slope Method= 1
Parabolic Critical Depth
Global Vel Dist=  1 , 1 , 1
Global Log Level= 0
CheckData=True
Encroach Param= -1, 0, 0, 0
BEGIN DESCRIPTION:
Multiple Run
END DESCRIPTION:

--- Chimney Creek 1113.f01 (steady flow) ---

Flow Title=Multiple
Number of Profiles=7
Profile Names=10-year,25-year,50-year,1pct_min,100-year,1pct_plu,500-year
River Rch & RM= Chimney Creek 11,Reach-1,5387
     212     288     350     212     423     844     625
River Rch & RM= Chimney Creek 11,Reach-1,4838
     318     441     543     333     664    1324    1004
River Rch & RM= Chimney Creek 11,Reach-1,25
    1352    1972    2508    1579    3151    6287    5039
Boundary for River Rch & Prof#=Chimney Creek 11,Reach-1,1
Up Type=0
Dn Type=3
Dn Slope=0.005
Boundary for River Rch & Prof#=Chimney Creek 11,Reach-1,2
Up Type=0
Dn Type=3
Dn Slope=0.005
Boundary for River Rch & Prof#=Chimney Creek 11,Reach-1,3
Up Type=0
Dn Type=3
Dn Slope=0.005
Boundary for River Rch & Prof#=Chimney Creek 11,Reach-1,4
Up Type=0
Dn Type=3
Dn Slope=0.005
Boundary for River Rch & Prof#=Chimney Creek 11,Reach-1,5
Up Type=0
Dn Type=3
Dn Slope=0.005
Boundary for River Rch & Prof#=Chimney Creek 11,Reach-1,6
Up Type=0
Dn Type=3
Dn Slope=0.005
Boundary for River Rch & Prof#=Chimney Creek 11,Reach-1,7
Up Type=0
Dn Type=3
Dn Slope=0.005

--- Chimney Creek 1113.g01 (geometry) ---

Geom Title=Existing Conditions

River Reach=Chimney Creek 11,Reach-1
Reach XY= 30
      1581055.00      6963638.00      1581147.11      6963734.66
      1581113.24      6963791.23      1581202.64      6963943.52
      1581212.68      6964094.52      1581532.29      6964264.10
      1581587.96      6964472.04      1581715.33      6964338.87
      1581950.04      6964393.11      1581908.12      6964586.38
      1582006.46      6964684.46      1582149.59      6964693.18
      1582205.29      6964808.16      1582156.73      6964932.38
      1582256.48      6965034.55      1582364.81      6965027.58
      1582560.88      6964789.96      1582732.19      6964838.38
      1582820.21      6964788.54      1583097.48      6964784.93
      1583008.00      6964589.40      1583205.10      6964495.34
      1583301.58      6964580.17      1583394.96      6964537.25
      1583494.97      6964577.93      1583456.04      6964827.58
      1583551.83      6964930.50      1583706.45      6964741.53
      1583955.01      6964695.51      1584105.00      6964738.00

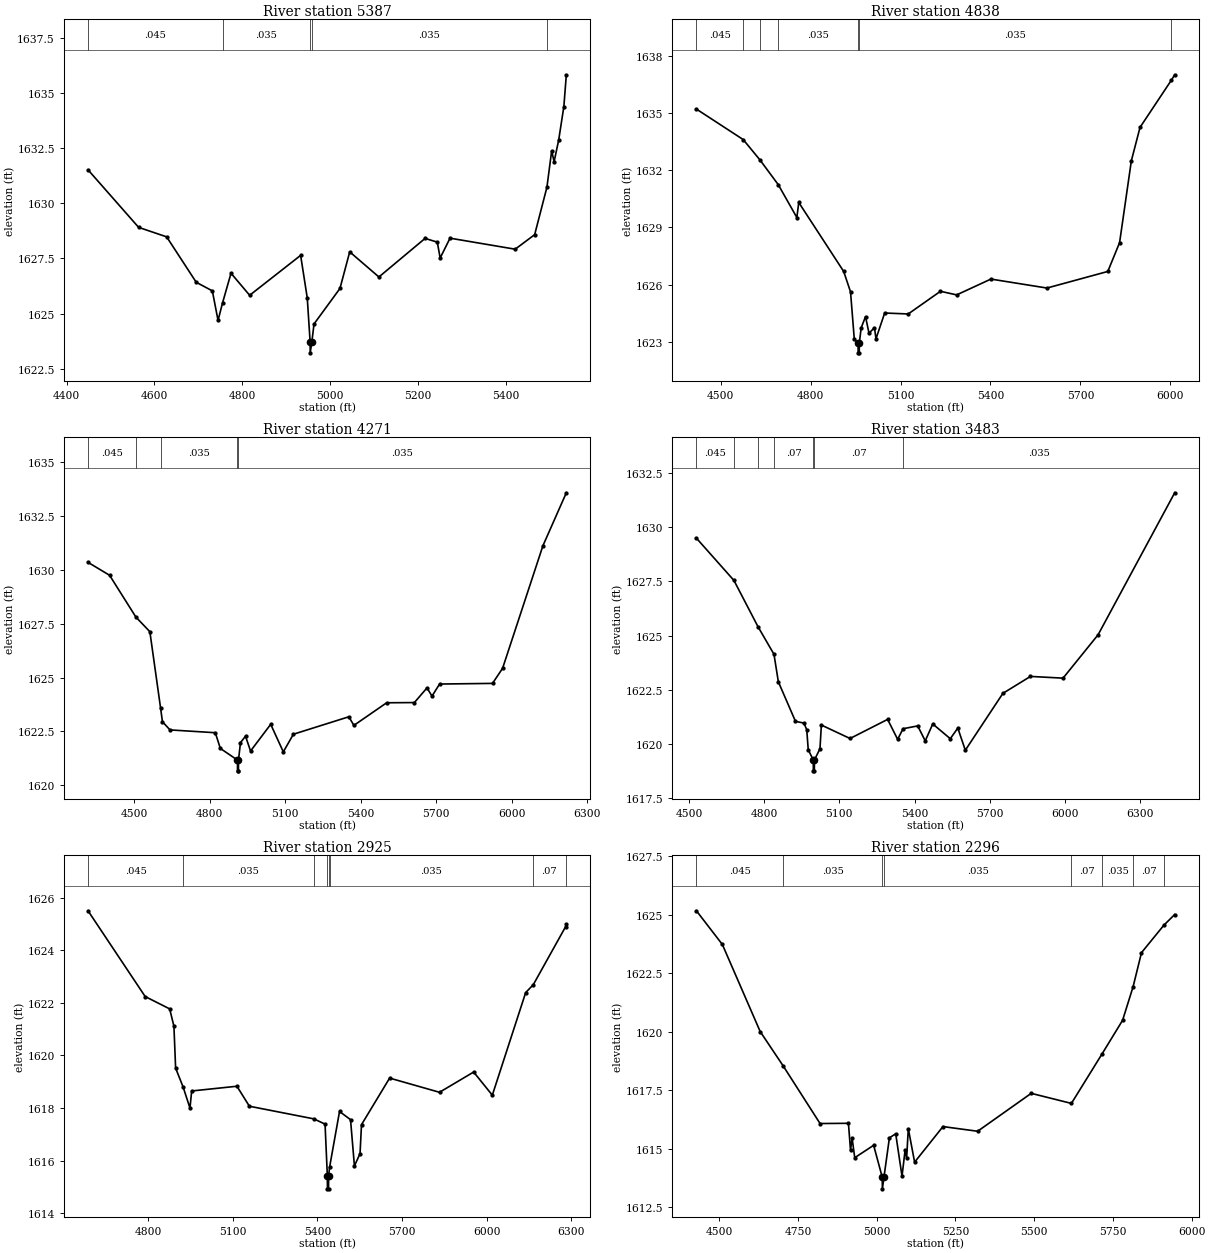
Type RM Length L Ch R = 1,5387,549,549,549
BEGIN DESCRIPTION:
Chimney Creek 1113 5.0
END DESCRIPTION:
XS GIS Cut Line= 3
      1580798.66      6964139.94      1581088.52      6963671.22
      1581334.87      6963192.49
#Sta/Elev= 30
  4448.9 1631.52  4564.2 1628.91  4628.0 1628.48  4695.4 1626.42  4732.1 1626.03
  4745.1 1624.69  4755.4 1625.49  4774.6 1626.83  4817.1 1625.83  4933.2 1627.64
  4948.3 1625.71  4954.8 1623.72  4955.0 1623.22  4958.8 1623.72  4963.7 1624.53
  5022.8 1626.14  5045.0 1627.80  5111.5 1626.66  5216.7 1628.41  5244.5 1628.24
  5251.0 1627.52  5273.5 1628.42  5421.9 1627.92  5466.3 1628.58  5494.2 1630.73
  5505.0 1632.38  5510.6 1631.89  5521.0 1632.87  5532.8 1634.39  5538.4 1635.83
#Mann=5,-1,0
  4448.9   0.045       0  4755.4   0.035       0  4954.8   0.035       0
  4958.8   0.035       0  5494.2    0.07       0
Bank Sta=4954.8,4958.8
Exp/Cntr=0.3,0.1

Type RM Length L Ch R = 1,4838,567,567,567
BEGIN DESCRIPTION:
Chimney Creek 1113 4.0
END DESCRIPTION:
XS GIS Cut Line= 3
      1580907.16      6964598.92      1581256.25      6964134.49
      1581530.13      6963157.66
#Sta/Elev= 30
  4419.0 1635.21  4575.1 1633.61  4630.6 1632.55  4691.8 1631.25  4754.1 1629.52
  4760.4 1630.31  4910.3 1626.69  4933.1 1625.62  4945.7 1623.13  4958.3 1622.92
  4958.6 1622.42  4962.1 1622.42  4962.4 1622.92  4968.6 1623.73  4983.1 1624.32
  4994.8 1623.45  5012.9 1623.74  5018.1 1623.16  5047.0 1624.51  5125.6 1624.46
  5233.1 1625.65  5287.1 1625.46  5401.4 1626.29  5588.3 1625.82  5791.3 1626.69
  5830.6 1628.20  5869.9 1632.50  5898.8 1634.25  6003.1 1636.72  6014.5 1637.01
#Mann=7,-1,0
  4419.0   0.045       0  4575.1   0.035       0  4630.6   0.045       0
  4691.8   0.035       0  4958.3   0.035       0  4962.4   0.035       0
  6003.1    0.07       0
Bank Sta=4958.3,4962.4
Exp/Cntr=0.3,0.1

Type RM Length L Ch R = 1,4271,788,788,788
BEGIN DESCRIPTION:
Mapping XS 8fa32713
END DESCRIPTION:
XS GIS Cut Line= 3
      1581616.81      6965163.62      1581603.79      6964481.28
      1581666.29      6963265.15
#Sta/Elev= 30
  4317.2 1630.35  4402.8 1629.75  4507.4 1627.81  4562.9 1627.13  4605.3 1623.60
  4612.9 1622.95  4642.9 1622.57  4822.9 1622.44  4842.9 1621.71  4910.9 1621.17
  4911.1 1620.67  4914.7 1620.67  4915.0 1621.17  4922.9 1621.98  4942.9 1622.28
  4962.9 1621.59  5043.0 1622.83  5093.1 1621.55  5133.1 1622.37  5353.4 1623.18
  5373.4 1622.78  5503.6 1623.83  5613.8 1623.84  5663.8 1624.52  5683.8 1624.14
  5713.9 1624.70  5924.2 1624.73  5964.2 1625.43  6124.4 1631.12  6217.4 1633.58
#Mann=5,-1,0
  4317.2   0.045       0  4507.4    0.07       0  4605.3   0.035       0
  4910.9   0.035       0  4915.0   0.035       0
Bank Sta=4910.9,4915
Exp/Cntr=0.3,0.1

Type RM Length L Ch R = 1,3483,558,558,558
BEGIN DESCRIPTION:
Mapping XS 24495975
END DESCRIPTION:
XS GIS Cut Line= 3
      1581799.12      6965106.24      1581999.62      6964681.80
      1582017.85      6963242.33
#Sta/Elev= 30
  4529.5 1629.49  4679.4 1627.54  4775.8 1625.40  4839.1 1624.14  4856.6 1622.87
  4924.9 1621.05  4958.9 1620.97  4969.9 1620.66  4975.9 1619.74  4996.0 1619.27
  4996.3 1618.77  5000.2 1618.77  5000.6 1619.27  5022.7 1619.79  5028.2 1620.88
  5142.7 1620.26  5292.7 1621.14  5332.7 1620.22  5354.3 1620.71  5412.8 1620.84
  5442.8 1620.15  5472.8 1620.93  5542.8 1620.25  5572.8 1620.74  5602.8 1619.72
  5752.8 1622.34  5862.8 1623.12  5992.8 1623.04  6132.8 1625.04  6438.5 1631.58
#Mann=7,-1,0
  4529.5   0.045       0  4679.4    0.07       0  4775.8   0.045       0
  4839.1    0.07       0  4996.0    0.07       0  5000.6    0.07       0
  5354.3   0.035       0
Bank Sta=4996,5000.6
Exp/Cntr=0.3,0.1

Type RM Length L Ch R = 1,2925,629,629,629
BEGIN DESCRIPTION:
Mapping XS 32f7be2a
END DESCRIPTION:
XS GIS Cut Line= 3
      1582016.74      6965371.30      1582245.93      6965032.72
      1582600.06      6963795.87
#Sta/Elev= 30
  4587.2 1625.50  4789.8 1622.24  4876.7 1621.77  4891.7 1621.11  4897.7 1619.52
  4924.3 1618.80  4948.6 1618.00  4954.6 1618.65  5115.0 1618.83  5159.2 1618.07
  5387.6 1617.59  5427.4 1617.39  5435.5 1615.43  5435.9 1614.93  5439.8 1614.93
  5440.1 1615.43  5443.6 1615.76  5478.7 1617.87  5517.7 1617.56  5531.5 1615.80
  5551.4 1616.27  5556.6 1617.37  5656.3 1619.14  5833.1 1618.60  5954.1 1619.37
  6020.3 1618.49  6138.5 1622.39  6165.5 1622.69  6279.8 1624.89  6282.6 1624.99
#Mann=8,-1,0
  4587.2   0.045       0  4924.3   0.035       0  5387.6    0.07       0
  5435.5   0.035       0  5440.1    0.07       0  5443.6   0.035       0
  6165.5    0.07       0  6279.8   0.035       0
Bank Sta=5435.5,5440.1
Exp/Cntr=0.3,0.1

Type RM Length L Ch R = 1,2296,724,724,724
BEGIN DESCRIPTION:
Mapping XS 35078998
END DESCRIPTION:
XS GIS Cut Line= 3
      1582712.08      6965410.37      1582732.91      6964840.01
      1582704.28      6963892.58
#Sta/Elev= 30
  4427.6 1625.16  4510.0 1623.72  4630.1 1620.00  4703.2 1618.53  4820.2 1616.07
  4910.3 1616.08  4916.9 1614.93  4921.9 1615.45  4930.3 1614.61  4990.3 1615.14
  5017.6 1613.78  5018.1 1613.28  5023.1 1613.78  5040.4 1615.46  5060.4 1615.63
  5080.4 1613.82  5090.1 1614.92  5095.1 1614.60  5100.4 1615.85  5120.4 1614.42
  5210.4 1615.94  5320.5 1615.74  5490.6 1617.36  5618.2 1616.93  5716.2 1619.06
  5780.7 1620.48  5814.2 1621.92  5840.7 1623.37  5912.2 1624.55  5946.2 1625.00
#Mann=8,-1,0
  4427.6   0.045       0  4703.2   0.035       0  5017.6   0.035       0
  5023.1   0.035       0  5618.2    0.07       0  5716.2   0.035       0
  5814.2    0.07       0  5912.2   0.035       0
Bank Sta=5017.6,5023.1
Exp/Cntr=0.3,0.1

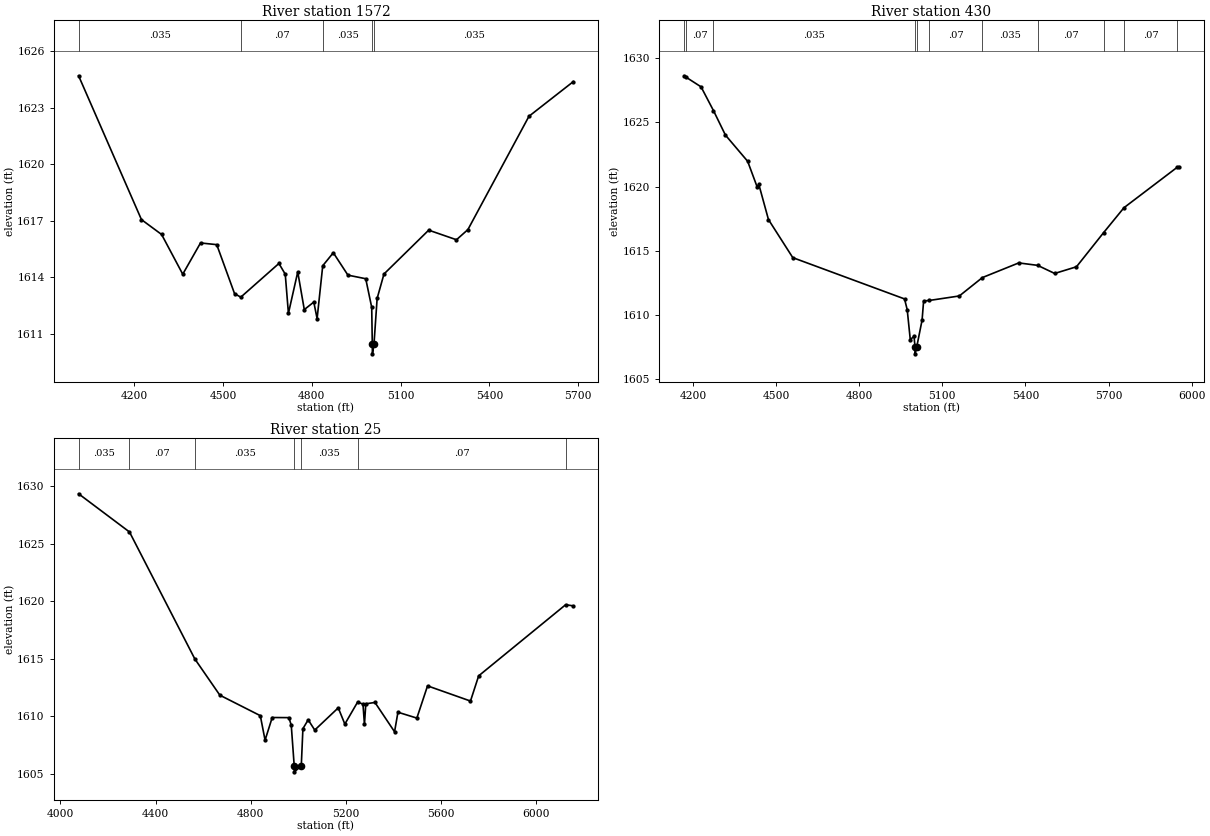
Type RM Length L Ch R = 1,1572,1142,1142,1142
BEGIN DESCRIPTION:
Mapping XS 5b0b5f9a
END DESCRIPTION:
XS GIS Cut Line= 3
      1583446.47      6965459.83      1583092.29      6964535.32
      1582871.53      6963891.24
#Sta/Elev= 30
  4012.6 1624.71  4224.9 1617.07  4293.0 1616.28  4364.4 1614.17  4424.4 1615.83
  4479.2 1615.74  4539.3 1613.14  4560.4 1612.95  4689.2 1614.74  4710.6 1614.17
  4721.3 1612.09  4752.8 1614.29  4774.9 1612.29  4807.0 1612.69  4818.2 1611.81
  4837.2 1614.62  4872.9 1615.31  4922.3 1614.12  4982.4 1613.93  5002.6 1612.41
  5004.6 1610.44  5005.0 1609.94  5010.2 1610.44  5020.9 1612.88  5044.0 1614.18
  5195.1 1616.51  5288.9 1616.00  5327.5 1616.54  5533.8 1622.56  5683.5 1624.40
#Mann=5,-1,0
  4012.6   0.035       0  4560.4    0.07       0  4837.2   0.035       0
  5004.6   0.035       0  5010.2   0.035       0
Bank Sta=5004.6,5010.2
Exp/Cntr=0.3,0.1

Type RM Length L Ch R = 1,430,405,405,405
BEGIN DESCRIPTION:
Mapping XS 538da03f
END DESCRIPTION:
XS GIS Cut Line= 3
      1583918.35      6965546.96      1583704.82      6964744.93
      1583285.53      6963885.52
#Sta/Elev= 30
  4167.7 1628.61  4173.1 1628.52  4228.7 1627.75  4273.6 1625.90  4316.7 1624.00
  4397.0 1621.96  4431.9 1619.93  4437.1 1620.18  4472.1 1617.43  4559.9 1614.47
  4963.4 1611.26  4973.1 1610.42  4984.1 1608.10  4997.7 1608.35  5001.4 1607.49
  5001.8 1606.99  5007.1 1607.49  5026.8 1609.62  5032.3 1611.10  5052.6 1611.14
  5161.2 1611.49  5244.5 1612.92  5375.8 1614.06  5443.9 1613.87  5505.5 1613.24
  5584.2 1613.76  5682.4 1616.42  5755.6 1618.35  5948.8 1621.51  5953.9 1621.54
#Mann=11,-1,0
  4167.7   0.035       0  4173.1    0.07       0  4273.6   0.035       0
  5001.4   0.035       0  5007.1   0.035       0  5052.6    0.07       0
  5244.5   0.035       0  5443.9    0.07       0  5682.4   0.035       0
  5755.6    0.07       0  5948.8   0.035       0
Bank Sta=5001.4,5007.1
Exp/Cntr=0.3,0.1

Type RM Length L Ch R = 1,25,0,0,0
BEGIN DESCRIPTION:
Chimney Creek 1113 1.0
END DESCRIPTION:
XS GIS Cut Line= 3
      1584085.03      6965661.55      1584080.00      6964738.26
      1583540.77      6963716.30
#Sta/Elev= 30
  4076.7 1629.35  4290.6 1626.03  4565.1 1615.00  4670.3 1611.85  4840.3 1610.07
  4860.3 1607.94  4890.3 1609.91  4960.3 1609.90  4970.3 1609.25  4982.8 1605.69
  4983.3 1605.19  5012.4 1605.69  5019.3 1608.94  5041.4 1609.71  5069.0 1608.82
  5167.8 1610.75  5195.5 1609.34  5248.8 1611.24  5271.7 1611.08  5277.9 1609.31
  5283.6 1611.10  5322.0 1611.22  5404.4 1608.67  5418.6 1610.37  5498.1 1609.86
  5543.0 1612.66  5723.4 1611.34  5757.8 1613.53  6123.3 1619.71  6155.5 1619.61
#Mann=7,-1,0
  4076.7   0.035       0  4290.6    0.07       0  4565.1   0.035       0
  4982.8   0.035       0  5012.4   0.035       0  5248.8    0.07       0
  6123.3   0.035       0
Bank Sta=4982.8,5012.4
Exp/Cntr=0.3,0.1

Chan Stop Cuts=-1