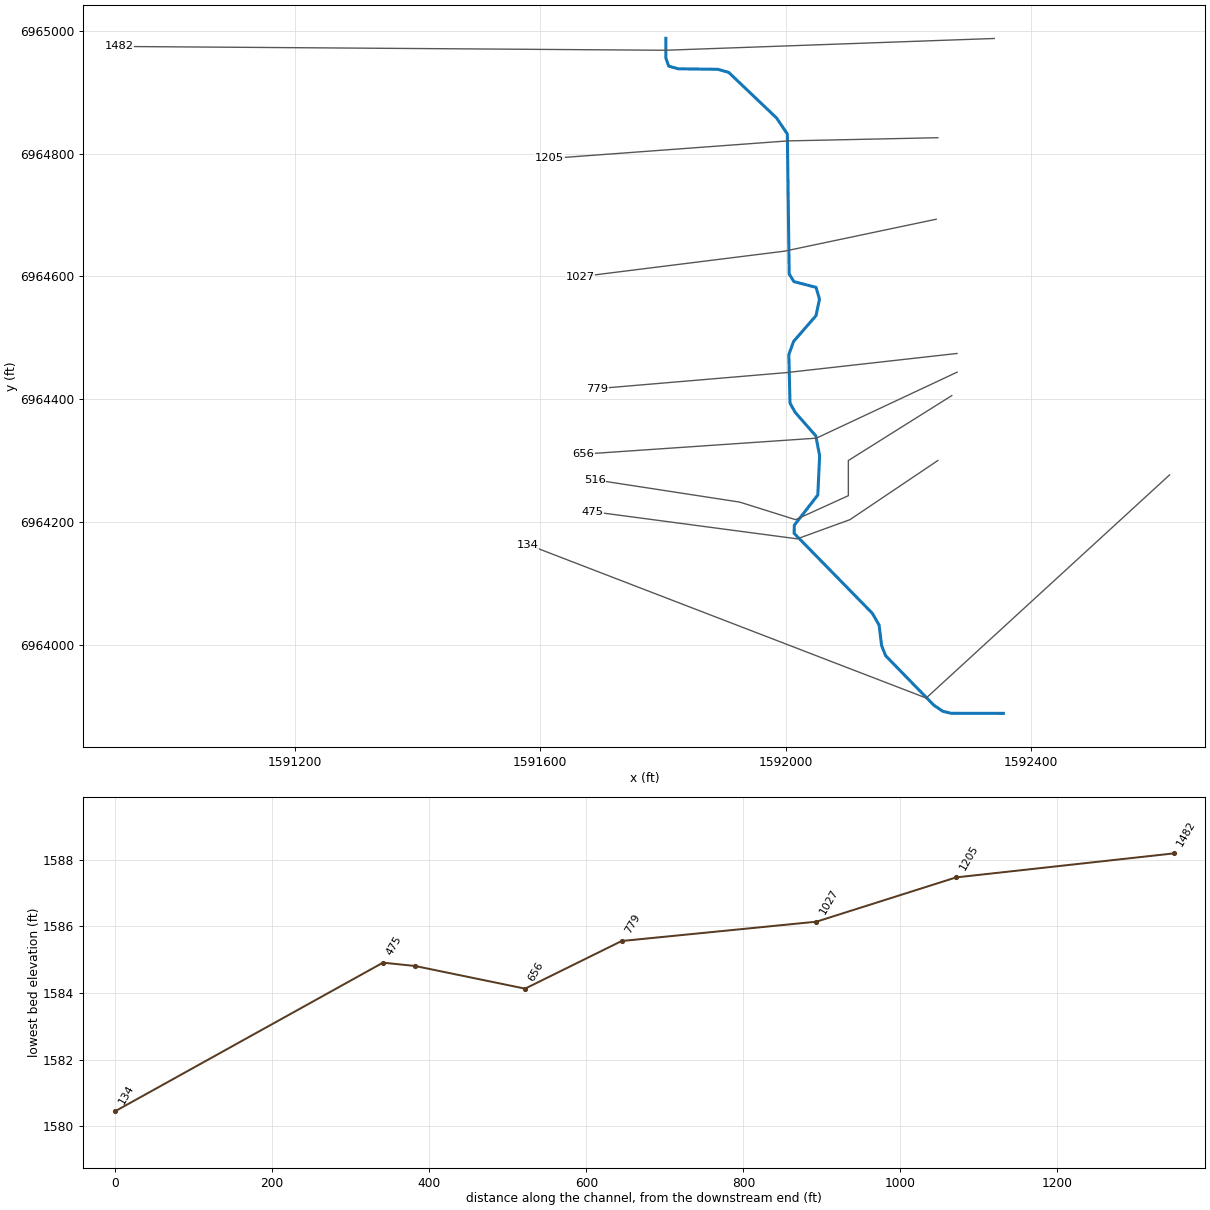
--- Chimney Creek 1114.prj (project) ---

Proj Title=Chimney Creek 1114 Base Level Engineering
Current Plan=p01
Default Exp/Contr=0.3,0.1
English Units
Geom File=g01
Flow File=f01
Plan File=p01
BEGIN DESCRIPTION:
Chimney Creek 1114
END DESCRIPTION:

--- Chimney Creek 1114.p01 (plan) ---

Plan Title=Multiple Run
Short Identifier=Multiple
Geom File=g01
Flow File=f01
Subcritical Flow
K Sum by GR= 0
Std Step Tol= 0.01
Critical Tol= 0.01
Num of Std Step Trials= 20
Max Error Tol= 0.3
Flow Tol Ratio= 0.001
Split Flow NTrial= 30
Split Flow Tol= 0.02
Split Flow Ratio= 0.02
Log Output Level= 0
Friction Slope Method= 1
Unsteady Friction Slope Method= 2
Unsteady Bridges Friction Slope Method= 1
Parabolic Critical Depth
Global Vel Dist=  1 , 1 , 1
Global Log Level= 0
CheckData=True
Encroach Param= -1, 0, 0, 0
BEGIN DESCRIPTION:
Multiple Run
END DESCRIPTION:

--- Chimney Creek 1114.f01 (steady flow) ---

Flow Title=Multiple
Number of Profiles=7
Profile Names=10-year,25-year,50-year,1pct_min,100-year,1pct_plu,500-year
River Rch & RM= Chimney Creek 11,Reach-1,1482
     205     278     337     204     407     812     600
Boundary for River Rch & Prof#=Chimney Creek 11,Reach-1,1
Up Type=0
Dn Type=3
Dn Slope=0.005
Boundary for River Rch & Prof#=Chimney Creek 11,Reach-1,2
Up Type=0
Dn Type=3
Dn Slope=0.005
Boundary for River Rch & Prof#=Chimney Creek 11,Reach-1,3
Up Type=0
Dn Type=3
Dn Slope=0.005
Boundary for River Rch & Prof#=Chimney Creek 11,Reach-1,4
Up Type=0
Dn Type=3
Dn Slope=0.005
Boundary for River Rch & Prof#=Chimney Creek 11,Reach-1,5
Up Type=0
Dn Type=3
Dn Slope=0.005
Boundary for River Rch & Prof#=Chimney Creek 11,Reach-1,6
Up Type=0
Dn Type=3
Dn Slope=0.005
Boundary for River Rch & Prof#=Chimney Creek 11,Reach-1,7
Up Type=0
Dn Type=3
Dn Slope=0.005

--- Chimney Creek 1114.g01 (geometry) ---

Geom Title=Existing Conditions

River Reach=Chimney Creek 11,Reach-1
Reach XY= 30
      1591805.00      6964988.00      1591804.92      6964956.10
      1591809.68      6964942.75      1591825.20      6964938.34
      1591889.74      6964937.55      1591907.42      6964932.51
      1591985.41      6964858.21      1592002.95      6964832.16
      1592006.00      6964603.94      1592013.68      6964591.55
      1592049.79      6964582.21      1592055.32      6964563.04
      1592049.72      6964536.13      1592013.15      6964494.10
      1592005.40      6964472.75      1592007.29      6964393.57
      1592015.82      6964378.37      1592049.31      6964340.31
      1592055.58      6964308.04      1592052.63      6964243.89
      1592014.29      6964194.53      1592014.13      6964181.26
      1592141.37      6964051.21      1592152.46      6964031.95
      1592156.54      6963998.63      1592163.15      6963981.93
      1592241.65      6963901.34      1592256.39      6963891.38
      1592270.04      6963888.11      1592355.00      6963888.00

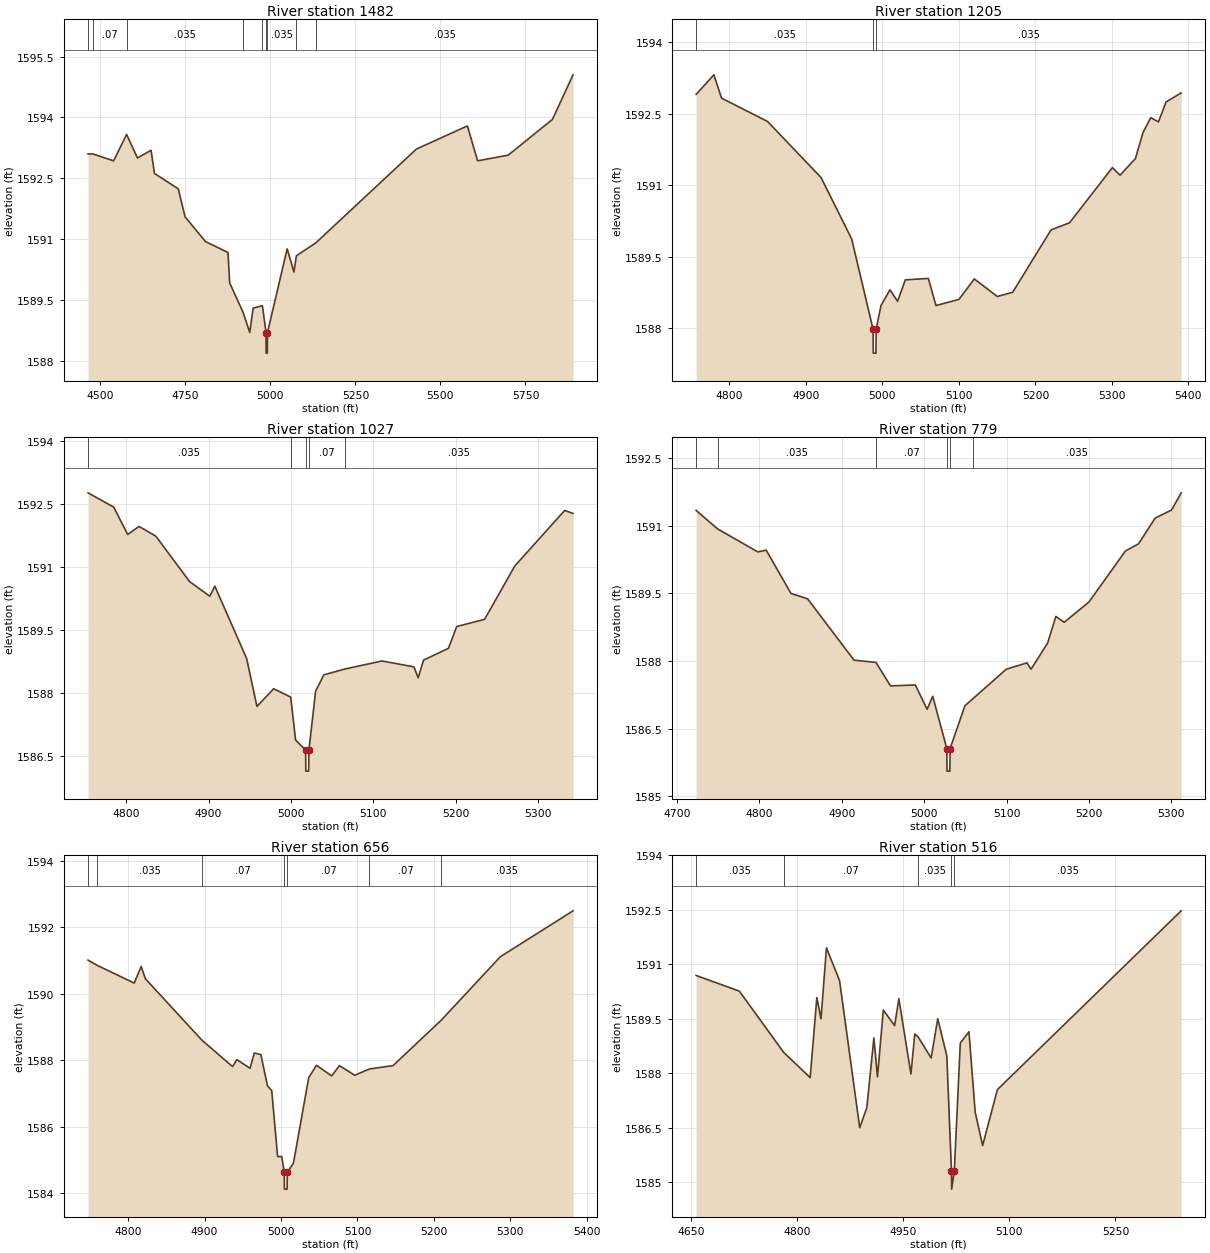
Type RM Length L Ch R = 1,1482,277,277,277
BEGIN DESCRIPTION:
Chimney Creek 1114 2.0
END DESCRIPTION:
XS GIS Cut Line= 3
      1592340.16      6964987.77      1591804.30      6964968.57
      1590914.33      6964974.75
#Sta/Elev= 30
  4463.8 1593.10  4478.2 1593.10  4539.0 1592.93  4577.2 1593.58  4609.1 1593.00
  4649.1 1593.19  4659.1 1592.62  4729.1 1592.24  4749.1 1591.55  4809.2 1590.94
  4875.3 1590.67  4880.3 1589.92  4919.5 1589.20  4939.3 1588.70  4949.3 1589.30
  4976.5 1589.36  4987.3 1588.69  4987.5 1588.19  4991.0 1588.19  4991.3 1588.69
  5049.3 1590.76  5069.3 1590.19  5076.5 1590.59  5133.9 1590.91  5429.3 1593.22
  5579.3 1593.79  5609.3 1592.93  5699.3 1593.07  5829.3 1593.95  5890.0 1595.05
#Mann=9,-1,0
  4463.8   0.045       0  4478.2    0.07       0  4577.2   0.035       0
  4919.5    0.07       0  4976.5   0.035       0  4987.3   0.035       0
  4991.3   0.035       0  5076.5    0.07       0  5133.9   0.035       0
Bank Sta=4987.3,4991.3
Exp/Cntr=0.3,0.1

Type RM Length L Ch R = 1,1205,178,178,178
BEGIN DESCRIPTION:
Mapping XS abc584c8
END DESCRIPTION:
XS GIS Cut Line= 3
      1592248.24      6964826.06      1592003.41      6964820.85
      1591615.35      6964792.20
#Sta/Elev= 30
  4756.5 1592.91  4779.7 1593.32  4789.7 1592.83  4849.8 1592.34  4919.8 1591.16
  4959.8 1589.87  4987.8 1587.97  4988.0 1587.47  4991.5 1587.47  4991.8 1587.97
  4998.1 1588.47  5009.8 1588.80  5019.8 1588.56  5029.9 1589.01  5060.0 1589.04
  5070.0 1588.47  5100.1 1588.60  5120.1 1589.03  5150.2 1588.66  5170.3 1588.75
  5220.4 1590.06  5244.6 1590.21  5300.6 1591.37  5310.6 1591.21  5330.7 1591.56
  5340.7 1592.11  5350.7 1592.42  5360.8 1592.33  5370.8 1592.75  5390.5 1592.94
#Mann=3,-1,0
  4756.5   0.035       0  4987.8   0.035       0  4991.8   0.035       0
Bank Sta=4987.8,4991.8
Exp/Cntr=0.3,0.1

Type RM Length L Ch R = 1,1027,248,248,248
BEGIN DESCRIPTION:
Mapping XS 69821659
END DESCRIPTION:
XS GIS Cut Line= 3
      1592245.56      6964693.23      1591998.20      6964641.16
      1591664.87      6964599.49
#Sta/Elev= 30
  4753.7 1592.76  4784.9 1592.42  4801.8 1591.77  4815.6 1591.96  4836.0 1591.73
  4876.9 1590.65  4901.5 1590.30  4907.6 1590.54  4946.2 1588.82  4958.7 1587.68
  4979.1 1588.10  4999.7 1587.90  5005.6 1586.88  5017.8 1586.64  5018.0 1586.14
  5021.5 1586.14  5021.8 1586.64  5029.9 1588.04  5039.9 1588.43  5065.6 1588.57
  5110.5 1588.76  5149.3 1588.62  5154.4 1588.36  5160.9 1588.78  5191.1 1589.06
  5201.2 1589.58  5235.0 1589.75  5271.7 1591.02  5332.2 1592.34  5342.4 1592.27
#Mann=5,-1,0
  4753.7   0.035       0  4999.7    0.07       0  5017.8    0.07       0
  5021.8    0.07       0  5065.6   0.035       0
Bank Sta=5017.8,5021.8
Exp/Cntr=0.3,0.1

Type RM Length L Ch R = 1,779,123,123,123
BEGIN DESCRIPTION:
Mapping XS 95e996fb
END DESCRIPTION:
XS GIS Cut Line= 3
      1592279.42      6964474.49      1592000.81      6964443.24
      1591693.47      6964417.20
#Sta/Elev= 30
  4723.1 1591.34  4749.1 1590.93  4798.0 1590.42  4808.1 1590.46  4838.2 1589.50
  4858.4 1589.38  4914.8 1588.02  4941.4 1587.97  4959.0 1587.45  4989.2 1587.47
  5003.5 1586.93  5010.3 1587.22  5027.4 1586.06  5027.6 1585.56  5031.1 1585.56
  5031.4 1586.06  5049.4 1587.01  5059.4 1587.17  5099.6 1587.82  5124.7 1587.96
  5129.7 1587.82  5149.8 1588.40  5159.8 1588.99  5169.9 1588.86  5200.0 1589.31
  5244.2 1590.44  5260.2 1590.60  5280.3 1591.17  5300.3 1591.35  5311.9 1591.73
#Mann=6,-1,0
  4723.1   0.045       0  4749.1   0.035       0  4941.4    0.07       0
  5027.4    0.07       0  5031.4    0.07       0  5059.4   0.035       0
Bank Sta=5027.4,5031.4
Exp/Cntr=0.3,0.1

Type RM Length L Ch R = 1,656,140,140,140
BEGIN DESCRIPTION:
Mapping XS 3aeee46a
END DESCRIPTION:
XS GIS Cut Line= 3
      1592279.68      6964444.05      1592050.29      6964336.47
      1591670.04      6964310.43
#Sta/Elev= 30
  4747.5 1591.01  4759.6 1590.85  4807.9 1590.32  4817.0 1590.82  4822.5 1590.45
  4896.7 1588.60  4936.6 1587.81  4942.2 1588.02  4959.5 1587.76  4965.0 1588.22
  4973.6 1588.17  4982.3 1587.23  4987.8 1587.09  4995.5 1585.11  5000.9 1585.11
  5004.2 1584.63  5004.4 1584.13  5007.9 1584.13  5008.2 1584.63  5016.2 1584.91
  5036.2 1587.48  5046.3 1587.85  5066.3 1587.53  5076.3 1587.84  5096.4 1587.55
  5115.7 1587.74  5146.5 1587.84  5209.8 1589.21  5286.8 1591.11  5382.0 1592.49
#Mann=7,-1,0
  4747.5   0.045       0  4759.6   0.035       0  4896.7    0.07       0
  5004.2    0.07       0  5008.2    0.07       0  5115.7    0.07       0
  5209.8   0.035       0
Bank Sta=5004.2,5008.2
Exp/Cntr=0.3,0.1

Type RM Length L Ch R = 1,516,41,41,41
BEGIN DESCRIPTION:
Mapping XS 536292aa
END DESCRIPTION:
XS GIS Cut Line= 6
      1592270.96      6964405.84      1592102.37      6964300.01
      1592102.37      6964242.72      1592016.43      6964203.66
      1591925.29      6964232.30      1591689.15      6964268.63
#Sta/Elev= 30
  4657.7 1590.69  4718.7 1590.26  4781.5 1588.57  4818.8 1587.88  4828.2 1590.08
  4834.1 1589.50  4841.8 1591.45  4860.3 1590.55  4888.8 1586.50  4898.8 1587.05
  4908.8 1588.97  4913.9 1587.90  4922.1 1589.74  4938.1 1589.31  4944.1 1590.05
  4961.1 1587.98  4966.6 1589.08  4971.3 1589.00  4989.7 1588.42  4999.0 1589.50
  5011.8 1588.48  5018.4 1585.31  5018.7 1584.81  5022.4 1585.31  5030.9 1588.83
  5043.1 1589.14  5051.9 1586.93  5062.4 1586.01  5083.3 1587.55  5342.9 1592.47
#Mann=5,-1,0
  4657.7   0.035       0  4781.5    0.07       0  4971.3   0.035       0
  5018.4   0.035       0  5022.4   0.035       0
Bank Sta=5018.4,5022.4
Exp/Cntr=0.3,0.1

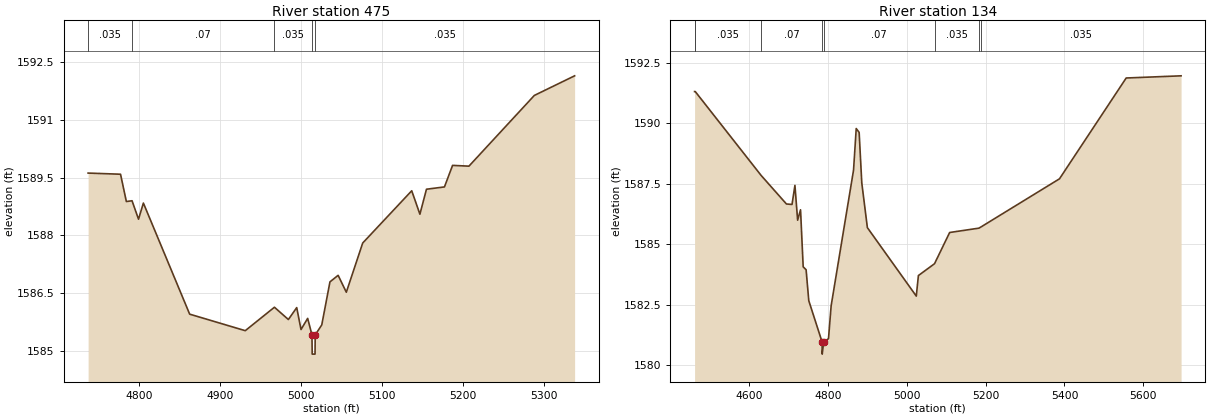
Type RM Length L Ch R = 1,475,341,341,341
BEGIN DESCRIPTION:
Mapping XS 0071b426
END DESCRIPTION:
XS GIS Cut Line= 4
      1592248.22      6964300.02      1592104.97      6964203.66
      1592019.04      6964172.41      1591685.75      6964216.67
#Sta/Elev= 30
  4737.0 1589.62  4777.0 1589.59  4784.2 1588.88  4791.2 1588.90  4799.2 1588.42
  4805.2 1588.84  4862.3 1585.95  4930.9 1585.52  4966.9 1586.13  4984.1 1585.81
  4994.4 1586.12  4999.7 1585.55  5007.9 1585.84  5013.2 1585.41  5013.5 1584.91
  5017.0 1584.91  5017.2 1585.41  5025.3 1585.67  5035.4 1586.79  5045.5 1586.96
  5055.6 1586.52  5075.8 1587.80  5136.3 1589.16  5146.4 1588.55  5154.5 1589.20
  5176.7 1589.26  5186.7 1589.82  5206.9 1589.80  5287.6 1591.64  5337.3 1592.15
#Mann=5,-1,0
  4737.0   0.035       0  4791.2    0.07       0  4966.9   0.035       0
  5013.2   0.035       0  5017.2   0.035       0
Bank Sta=5013.2,5017.2
Exp/Cntr=0.3,0.1

Type RM Length L Ch R = 1,134,0,0,0
BEGIN DESCRIPTION:
Chimney Creek 1114 1.0
END DESCRIPTION:
XS GIS Cut Line= 3
      1592625.81      6964276.58      1592229.26      6963913.00
      1591580.03      6964162.99
#Sta/Elev= 30
  4462.0 1591.31  4463.7 1591.31  4630.8 1587.84  4694.9 1586.66  4709.1 1586.64
  4716.5 1587.43  4723.3 1585.99  4730.7 1586.42  4737.4 1584.06  4744.8 1583.94
  4751.6 1582.66  4785.4 1580.95  4785.6 1580.45  4789.4 1580.95  4801.6 1581.09
  4808.3 1582.45  4865.1 1588.06  4871.9 1589.78  4879.3 1589.62  4886.0 1587.53
  4900.2 1585.68  5024.2 1582.85  5029.6 1583.70  5070.5 1584.19  5108.8 1585.48
  5183.0 1585.66  5189.3 1585.72  5387.3 1587.70  5556.5 1591.87  5695.7 1591.96
#Mann=8,-1,0
  4462.0   0.045       0  4463.7   0.035       0  4630.8    0.07       0
  4785.4    0.07       0  4789.4    0.07       0  5070.5   0.035       0
  5183.0    0.07       0  5189.3   0.035       0
Bank Sta=4785.4,4789.4
Exp/Cntr=0.3,0.1

Chan Stop Cuts=-1