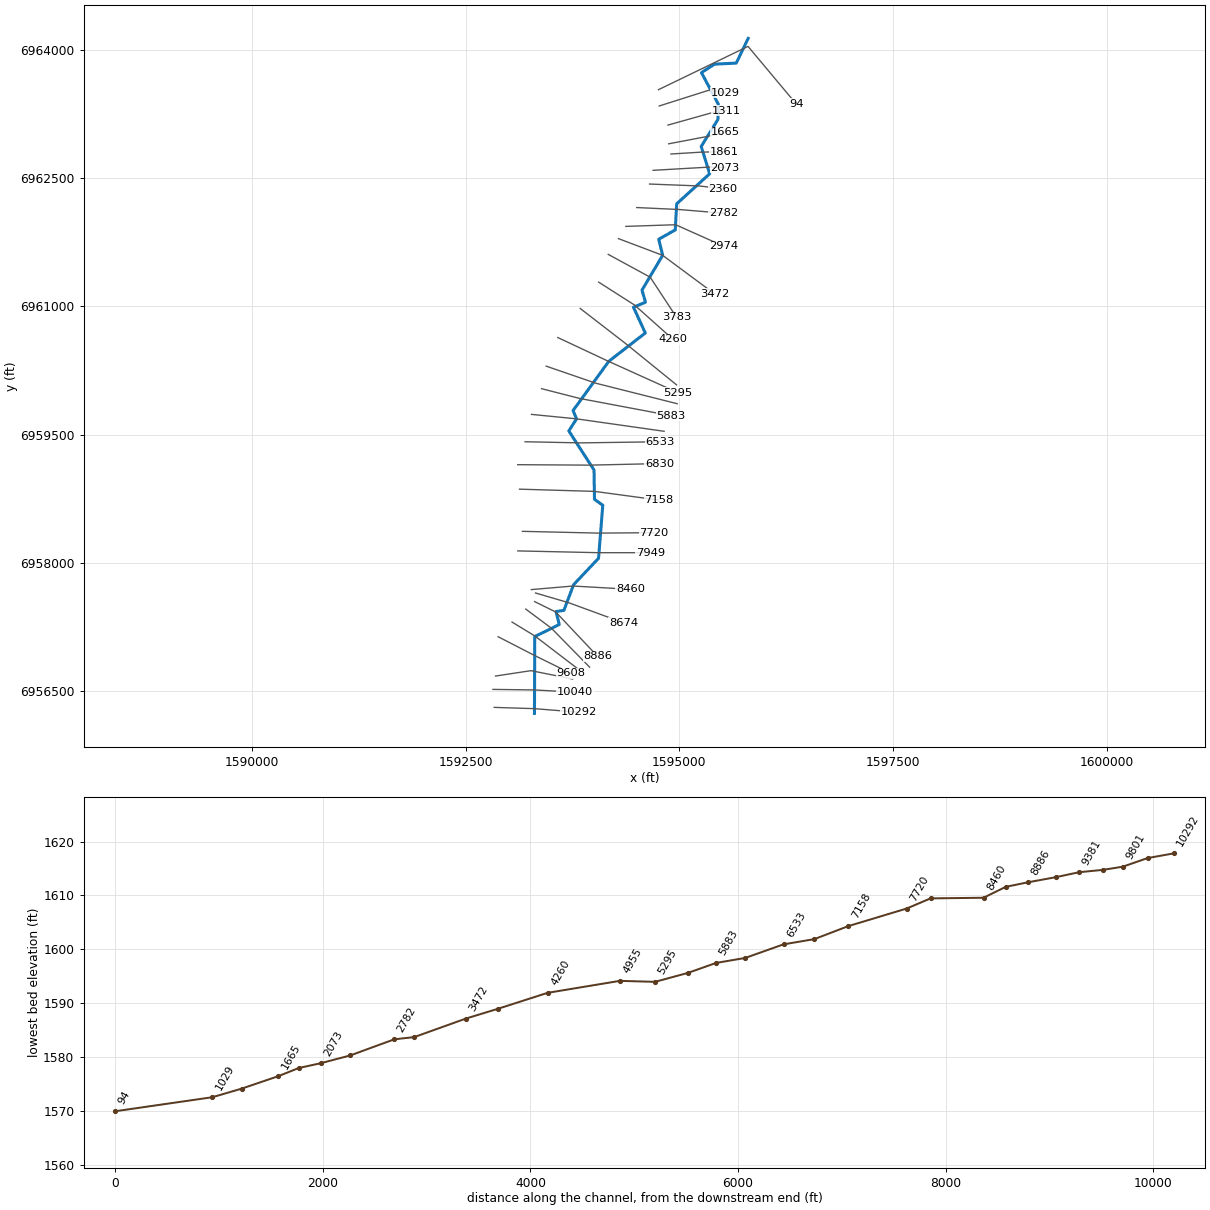
--- Chimney Creek 1116.prj (project) ---

Proj Title=Chimney Creek 1116 Base Level Engineering
Current Plan=p01
Default Exp/Contr=0.3,0.1
English Units
Geom File=g01
Flow File=f01
Plan File=p01
BEGIN DESCRIPTION:
Chimney Creek 1116
END DESCRIPTION:

--- Chimney Creek 1116.p01 (plan) ---

Plan Title=Multiple Run
Short Identifier=Multiple
Geom File=g01
Flow File=f01
Subcritical Flow
K Sum by GR= 0
Std Step Tol= 0.01
Critical Tol= 0.01
Num of Std Step Trials= 20
Max Error Tol= 0.3
Flow Tol Ratio= 0.001
Split Flow NTrial= 30
Split Flow Tol= 0.02
Split Flow Ratio= 0.02
Log Output Level= 0
Friction Slope Method= 1
Unsteady Friction Slope Method= 2
Unsteady Bridges Friction Slope Method= 1
Parabolic Critical Depth
Global Vel Dist=  1 , 1 , 1
Global Log Level= 0
CheckData=True
Encroach Param= -1, 0, 0, 0
BEGIN DESCRIPTION:
Multiple Run
END DESCRIPTION:

--- Chimney Creek 1116.f01 (steady flow) ---

Flow Title=Multiple
Number of Profiles=7
Profile Names=10-year,25-year,50-year,1pct_min,100-year,1pct_plu,500-year
River Rch & RM= Chimney Creek 11,Reach-1,10292
     249     345     425     260     520    1037     788
River Rch & RM= Chimney Creek 11,Reach-1,7949
     339     476     590     364     726    1448    1113
Boundary for River Rch & Prof#=Chimney Creek 11,Reach-1,1
Up Type=0
Dn Type=3
Dn Slope=0.005
Boundary for River Rch & Prof#=Chimney Creek 11,Reach-1,2
Up Type=0
Dn Type=3
Dn Slope=0.005
Boundary for River Rch & Prof#=Chimney Creek 11,Reach-1,3
Up Type=0
Dn Type=3
Dn Slope=0.005
Boundary for River Rch & Prof#=Chimney Creek 11,Reach-1,4
Up Type=0
Dn Type=3
Dn Slope=0.005
Boundary for River Rch & Prof#=Chimney Creek 11,Reach-1,5
Up Type=0
Dn Type=3
Dn Slope=0.005
Boundary for River Rch & Prof#=Chimney Creek 11,Reach-1,6
Up Type=0
Dn Type=3
Dn Slope=0.005
Boundary for River Rch & Prof#=Chimney Creek 11,Reach-1,7
Up Type=0
Dn Type=3
Dn Slope=0.005

--- Chimney Creek 1116.g01 (geometry) ---

Geom Title=Existing Conditions

River Reach=Chimney Creek 11,Reach-1
Reach XY= 30
      1593305.00      6956238.00      1593308.44      6957136.78
      1593594.94      6957278.00      1593557.56      6957429.82
      1593649.44      6957443.29      1593762.82      6957744.19
      1594054.62      6958053.16      1594104.11      6958673.29
      1594007.01      6958743.68      1594001.45      6959086.53
      1593706.70      6959543.64      1593797.16      6959684.60
      1593756.84      6959781.88      1594174.58      6960358.57
      1594601.54      6960689.50      1594462.65      6960991.67
      1594603.60      6961049.58      1594562.81      6961191.41
      1594804.40      6961598.62      1594758.37      6961786.72
      1594951.78      6961895.99      1594968.64      6962201.34
      1595354.12      6962552.71      1595255.36      6962872.73
      1595451.45      6963189.47      1595455.04      6963368.02
      1595258.01      6963736.57      1595410.52      6963835.65
      1595665.12      6963848.34      1595805.00      6964138.00

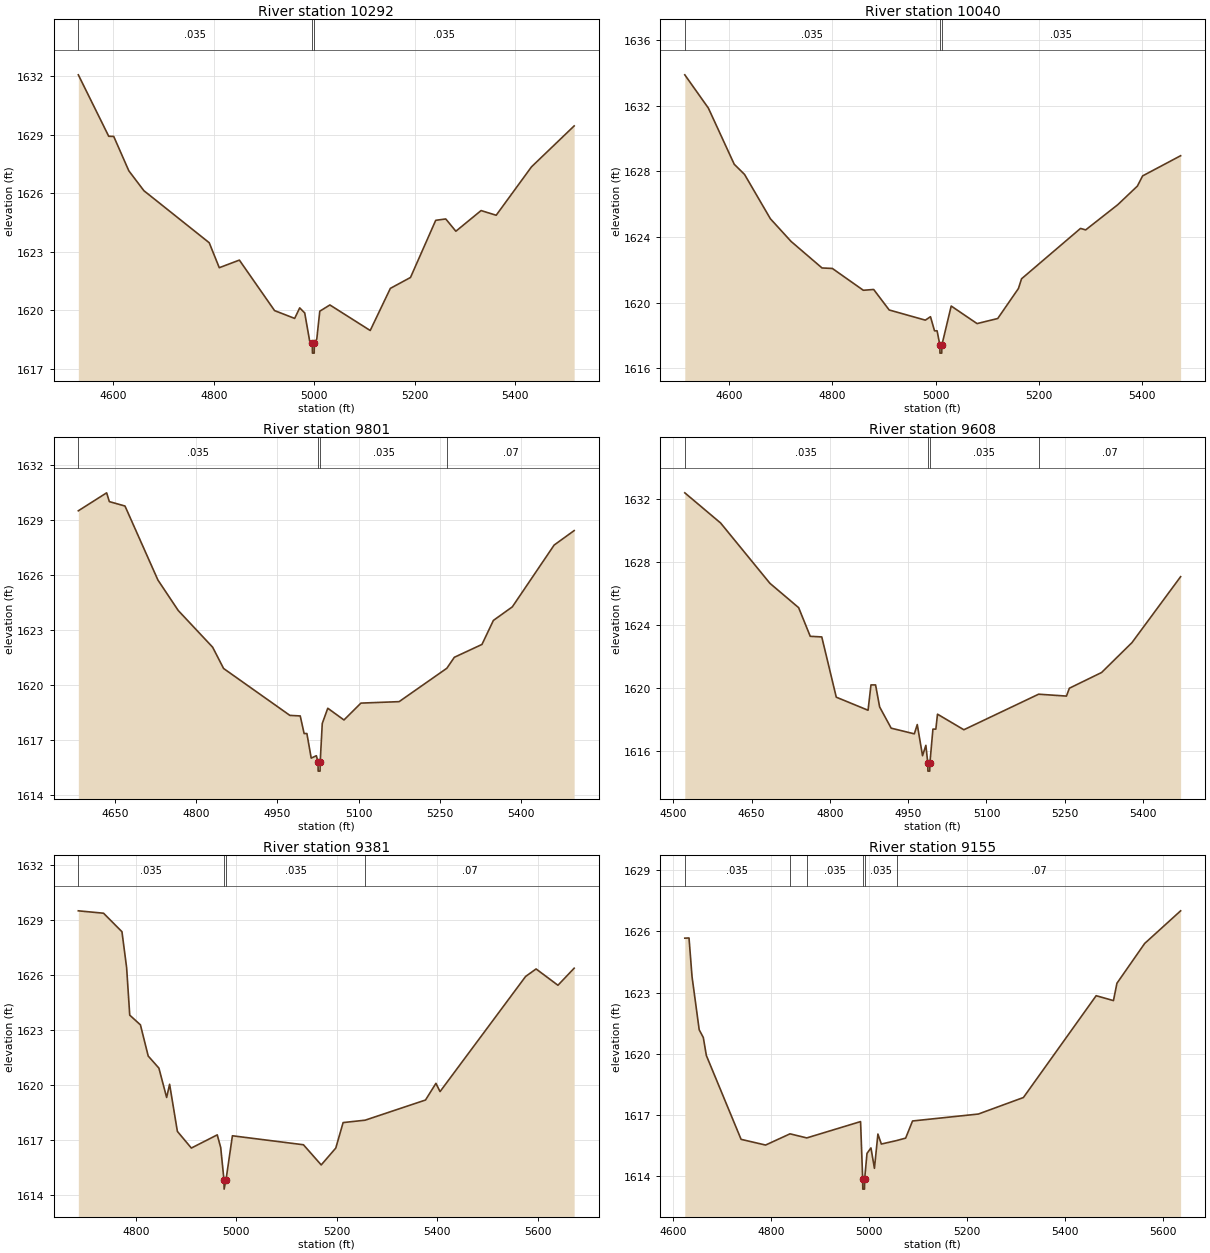
Type RM Length L Ch R = 1,10292,252,252,252
BEGIN DESCRIPTION:
Chimney Creek 1116 12.0
END DESCRIPTION:
XS GIS Cut Line= 3
      1592834.54      6956308.18      1593304.31      6956293.29
      1593819.74      6956251.76
#Sta/Elev= 30
  4530.0 1632.06  4590.5 1628.91  4600.5 1628.90  4630.5 1627.14  4660.5 1626.12
  4790.6 1623.45  4810.6 1622.17  4850.6 1622.56  4920.7 1619.97  4960.7 1619.57
  4970.7 1620.11  4980.7 1619.85  4990.7 1618.39  4995.8 1618.29  4996.1 1617.79
  4999.6 1617.79  4999.8 1618.29  5004.7 1618.51  5010.7 1619.94  5030.8 1620.26
  5111.1 1618.95  5151.2 1621.11  5191.3 1621.67  5241.5 1624.60  5261.5 1624.67
  5281.6 1624.04  5331.8 1625.10  5361.9 1624.86  5432.1 1627.34  5517.1 1629.44
#Mann=3,-1,0
  4530.0   0.035       0  4995.8   0.035       0  4999.8   0.035       0
Bank Sta=4995.8,4999.8
Exp/Cntr=0.3,0.1

Type RM Length L Ch R = 1,10040,239,239,239
BEGIN DESCRIPTION:
Mapping XS d2a9a289
END DESCRIPTION:
XS GIS Cut Line= 3
      1592819.30      6956518.68      1593305.44      6956512.17
      1593778.54      6956486.13
#Sta/Elev= 30
  4514.4 1633.88  4560.1 1631.85  4610.1 1628.43  4630.1 1627.81  4680.1 1625.11
  4720.1 1623.73  4780.1 1622.11  4800.1 1622.08  4860.1 1620.75  4880.1 1620.80
  4910.1 1619.55  4980.1 1618.93  4990.1 1619.14  4997.9 1618.28  5002.9 1618.28
  5008.2 1617.42  5008.4 1616.92  5011.9 1616.92  5012.2 1617.42  5030.2 1619.79
  5080.3 1618.72  5120.3 1619.03  5160.4 1620.86  5166.4 1621.45  5280.6 1624.52
  5290.6 1624.43  5352.5 1625.96  5390.7 1627.10  5400.8 1627.72  5474.4 1628.95
#Mann=3,-1,0
  4514.4   0.035       0  5008.2   0.035       0  5012.2   0.035       0
Bank Sta=5008.2,5012.2
Exp/Cntr=0.3,0.1

Type RM Length L Ch R = 1,9801,193,193,193
BEGIN DESCRIPTION:
Mapping XS 2ff577a8
END DESCRIPTION:
XS GIS Cut Line= 3
      1592849.75      6956674.94      1593264.20      6956737.87
      1593751.26      6956640.46
#Sta/Elev= 30
  4582.4 1629.52  4634.7 1630.50  4639.7 1630.02  4668.6 1629.78  4729.3 1625.75
  4767.0 1624.08  4830.5 1622.08  4850.7 1620.92  4973.2 1618.36  4992.3 1618.33
  4999.5 1617.37  5004.6 1617.37  5012.6 1616.03  5022.1 1616.16  5025.2 1615.82
  5025.4 1615.32  5028.9 1615.32  5029.2 1615.82  5033.0 1617.92  5043.2 1618.75
  5073.1 1618.11  5104.4 1619.03  5175.0 1619.11  5263.1 1620.93  5277.0 1621.53
  5328.0 1622.23  5349.1 1623.54  5384.1 1624.28  5461.3 1627.65  5498.3 1628.44
#Mann=4,-1,0
  4582.4   0.035       0  5025.2   0.035       0  5029.2   0.035       0
  5263.1    0.07       0
Bank Sta=5025.2,5029.2
Exp/Cntr=0.3,0.1

Type RM Length L Ch R = 1,9608,227,227,227
BEGIN DESCRIPTION:
Mapping XS 81f5fdfe
END DESCRIPTION:
XS GIS Cut Line= 3
      1592880.04      6957135.02      1593305.44      6956915.82
      1593728.59      6956707.50
#Sta/Elev= 30
  4521.9 1632.42  4590.6 1630.50  4685.0 1626.67  4740.1 1625.12  4762.3 1623.30
  4784.4 1623.26  4812.2 1619.43  4873.1 1618.60  4878.7 1620.21  4887.5 1620.21
  4895.3 1618.81  4917.4 1617.46  4961.8 1617.10  4967.4 1617.69  4977.5 1615.71
  4983.9 1616.37  4987.6 1615.23  4987.8 1614.73  4991.3 1614.73  4991.6 1615.23
  4997.4 1617.40  5003.0 1617.40  5006.2 1618.35  5056.7 1617.36  5200.0 1619.62
  5253.3 1619.50  5258.9 1620.00  5320.7 1621.00  5378.9 1622.90  5472.1 1627.09
#Mann=4,-1,0
  4521.9   0.035       0  4987.6   0.035       0  4991.6   0.035       0
  5200.0    0.07       0
Bank Sta=4987.6,4991.6
Exp/Cntr=0.3,0.1

Type RM Length L Ch R = 1,9381,226,226,226
BEGIN DESCRIPTION:
Mapping XS 32a3274b
END DESCRIPTION:
XS GIS Cut Line= 3
      1593042.83      6957306.46      1593309.78      6957143.68
      1593845.80      6956733.53
#Sta/Elev= 30
  4685.3 1629.48  4735.5 1629.35  4772.2 1628.34  4781.5 1626.38  4787.7 1623.79
  4809.0 1623.26  4824.5 1621.56  4845.8 1620.90  4861.2 1619.30  4867.1 1620.02
  4882.6 1617.45  4910.4 1616.54  4962.0 1617.26  4968.9 1616.57  4975.4 1614.80
  4975.7 1614.30  4979.4 1614.80  4992.2 1617.21  5133.7 1616.72  5169.1 1615.62
  5198.1 1616.54  5212.7 1617.93  5256.5 1618.06  5376.8 1619.16  5397.6 1620.07
  5405.8 1619.62  5576.2 1625.90  5597.1 1626.31  5640.6 1625.42  5672.9 1626.35
#Mann=4,-1,0
  4685.3   0.035       0  4975.4   0.035       0  4979.4   0.035       0
  5256.5    0.07       0
Bank Sta=4975.4,4979.4
Exp/Cntr=0.3,0.1

Type RM Length L Ch R = 1,9155,269,269,269
BEGIN DESCRIPTION:
Mapping XS 5b25a25a
END DESCRIPTION:
XS GIS Cut Line= 3
      1593203.43      6957458.36      1593502.92      6957234.83
      1593949.97      6956779.10
#Sta/Elev= 30
  4623.5 1625.67  4632.1 1625.68  4638.3 1623.78  4652.9 1621.18  4661.3 1620.80
  4667.5 1619.92  4738.4 1615.81  4788.4 1615.53  4838.3 1616.08  4872.5 1615.88
  4982.3 1616.68  4986.6 1613.87  4986.8 1613.37  4990.3 1613.37  4990.6 1613.87
  4995.4 1615.12  5003.5 1615.39  5010.6 1614.39  5017.7 1616.07  5024.7 1615.58
  5055.8 1615.75  5074.3 1615.87  5088.4 1616.71  5222.7 1617.05  5314.7 1617.86
  5463.2 1622.85  5498.5 1622.61  5505.6 1623.46  5562.2 1625.41  5635.6 1627.01
#Mann=6,-1,0
  4623.5   0.035       0  4838.3    0.07       0  4872.5   0.035       0
  4986.6   0.035       0  4990.6   0.035       0  5055.8    0.07       0
Bank Sta=4986.6,4990.6
Exp/Cntr=0.3,0.1

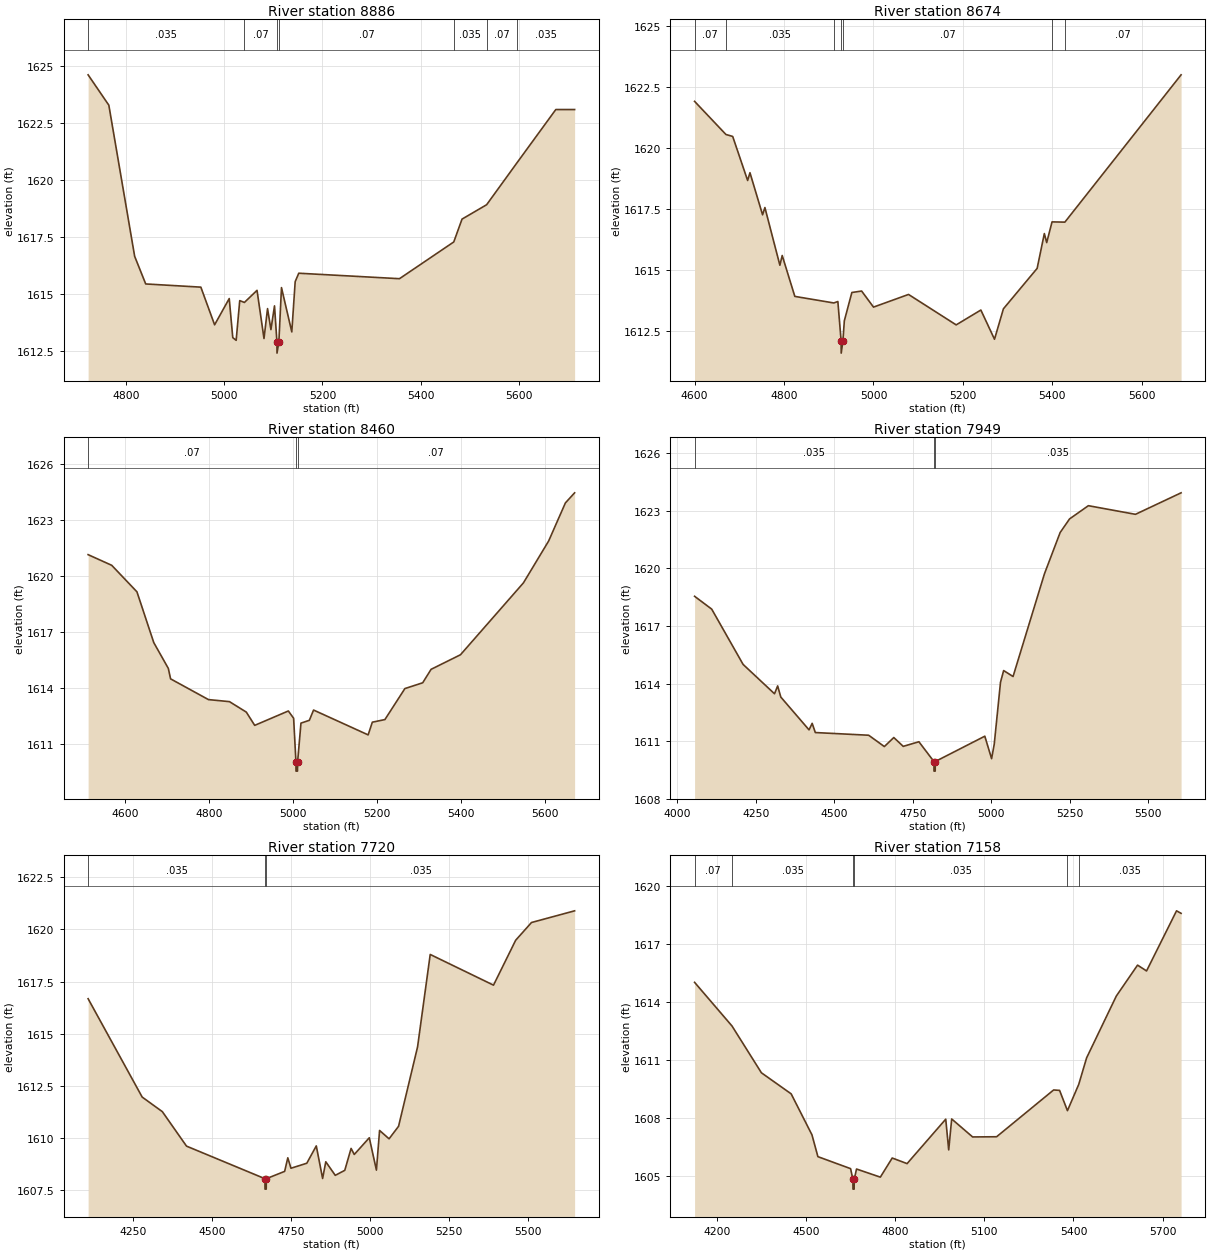
Type RM Length L Ch R = 1,8886,212,212,212
BEGIN DESCRIPTION:
Mapping XS 1fb83b2f
END DESCRIPTION:
XS GIS Cut Line= 3
      1593307.17      6957546.04      1593553.66      6957424.53
      1594044.97      6956903.71
#Sta/Elev= 30
  4722.8 1624.61  4765.0 1623.28  4817.6 1616.66  4840.1 1615.45  4952.4 1615.31
  4980.4 1613.66  5010.2 1614.81  5017.4 1613.10  5024.3 1612.98  5031.6 1614.72
  5041.1 1614.64  5066.8 1615.17  5081.0 1613.06  5088.2 1614.37  5095.1 1613.45
  5102.4 1614.49  5107.3 1612.92  5107.5 1612.42  5111.3 1612.92  5116.6 1615.29
  5137.6 1613.35  5144.5 1615.55  5151.8 1615.92  5356.9 1615.68  5467.5 1617.29
  5484.3 1618.29  5534.4 1618.92  5596.0 1620.75  5675.3 1623.09  5713.6 1623.09
#Mann=7,-1,0
  4722.8   0.035       0  5041.1    0.07       0  5107.3   0.035       0
  5111.3    0.07       0  5467.5   0.035       0  5534.4    0.07       0
  5596.0   0.035       0
Bank Sta=5107.3,5111.3
Exp/Cntr=0.3,0.1

Type RM Length L Ch R = 1,8674,214,214,214
BEGIN DESCRIPTION:
Mapping XS f3099808
END DESCRIPTION:
XS GIS Cut Line= 3
      1593317.59      6957646.74      1593702.97      6957533.91
      1594347.10      6957297.79
#Sta/Elev= 30
  4600.1 1621.92  4670.2 1620.56  4685.3 1620.48  4718.7 1618.67  4723.9 1618.99
  4752.1 1617.26  4757.3 1617.56  4790.8 1615.19  4796.0 1615.59  4824.2 1613.91
  4911.4 1613.64  4920.4 1613.70  4927.7 1612.08  4927.9 1611.58  4931.7 1612.08
  4934.9 1612.91  4951.7 1614.07  4973.5 1614.13  5000.1 1613.47  5078.4 1613.99
  5184.9 1612.74  5240.1 1613.35  5270.6 1612.15  5290.5 1613.40  5365.9 1615.06
  5382.0 1616.49  5387.3 1616.12  5399.2 1616.97  5427.9 1616.96  5687.7 1623.01
#Mann=7,-1,0
  4600.1    0.07       0  4670.2   0.035       0  4911.4    0.07       0
  4927.7    0.07       0  4931.7    0.07       0  5399.2   0.035       0
  5427.9    0.07       0
Bank Sta=4927.7,4931.7
Exp/Cntr=0.3,0.1

Type RM Length L Ch R = 1,8460,511,511,511
BEGIN DESCRIPTION:
Mapping XS 452144f0
END DESCRIPTION:
XS GIS Cut Line= 3
      1593268.90      6957686.68      1593755.05      6957728.35
      1594426.94      6957690.16
#Sta/Elev= 30
  4510.9 1621.15  4567.2 1620.58  4627.4 1619.16  4667.6 1616.44  4702.3 1615.06
  4707.7 1614.50  4798.0 1613.39  4848.2 1613.28  4888.4 1612.72  4908.4 1612.01
  4988.7 1612.78  5001.3 1612.39  5006.8 1610.06  5007.0 1609.56  5010.5 1609.56
  5010.8 1610.06  5018.8 1612.13  5038.8 1612.28  5048.9 1612.83  5179.1 1611.50
  5189.1 1612.18  5219.1 1612.32  5266.8 1613.98  5309.3 1614.29  5329.3 1615.01
  5399.4 1615.79  5549.7 1619.64  5609.8 1621.88  5649.8 1623.92  5671.8 1624.46
#Mann=3,-1,0
  4510.9    0.07       0  5006.8    0.07       0  5010.8    0.07       0
Bank Sta=5006.8,5010.8
Exp/Cntr=0.3,0.1

Type RM Length L Ch R = 1,7949,229,229,229
BEGIN DESCRIPTION:
Mapping XS a33f3dc5
END DESCRIPTION:
XS GIS Cut Line= 3
      1593110.40      6958139.29      1594056.62      6958118.46
      1594660.37      6958118.46
#Sta/Elev= 30
  4055.0 1618.55  4109.6 1617.88  4209.6 1615.00  4309.7 1613.47  4319.7 1613.88
  4329.7 1613.30  4419.7 1611.59  4429.7 1611.93  4439.7 1611.45  4609.7 1611.31
  4659.7 1610.72  4689.8 1611.19  4719.8 1610.73  4769.8 1610.97  4817.6 1609.94
  4817.9 1609.44  4821.7 1609.44  4821.9 1609.94  4979.8 1611.26  5001.4 1610.09
  5009.8 1610.84  5029.8 1614.07  5039.8 1614.68  5069.8 1614.37  5169.8 1619.72
  5219.8 1621.87  5249.8 1622.58  5309.8 1623.27  5459.8 1622.82  5605.2 1623.94
#Mann=3,-1,0
  4055.0   0.035       0  4817.6   0.035       0  4821.9   0.035       0
Bank Sta=4817.6,4821.9
Exp/Cntr=0.3,0.1

Type RM Length L Ch R = 1,7720,562,562,562
BEGIN DESCRIPTION:
Mapping XS b40a5c21
END DESCRIPTION:
XS GIS Cut Line= 3
      1593164.22      6958368.46      1594054.88      6958347.62
      1594701.25      6958352.82
#Sta/Elev= 30
  4109.0 1616.68  4279.8 1611.97  4343.6 1611.27  4419.9 1609.62  4667.7 1608.06
  4668.0 1607.56  4671.8 1607.56  4672.1 1608.06  4730.0 1608.41  4740.0 1609.06
  4750.0 1608.56  4800.0 1608.80  4830.0 1609.63  4850.0 1608.07  4860.0 1608.87
  4890.0 1608.22  4920.0 1608.46  4940.0 1609.51  4950.0 1609.22  4997.5 1610.02
  5020.0 1608.47  5030.0 1610.37  5060.0 1609.97  5090.0 1610.57  5150.0 1614.37
  5190.0 1618.80  5390.0 1617.33  5460.0 1619.48  5510.0 1620.33  5646.3 1620.89
#Mann=3,-1,0
  4109.0   0.035       0  4667.7   0.035       0  4672.1   0.035       0
Bank Sta=4667.7,4672.1
Exp/Cntr=0.3,0.1

Type RM Length L Ch R = 1,7158,328,328,328
BEGIN DESCRIPTION:
Mapping XS e6ecc845
END DESCRIPTION:
XS GIS Cut Line= 3
      1593130.19      6958861.97      1594007.82      6958835.93
      1594760.19      6958734.40
#Sta/Elev= 30
  4124.9 1615.00  4250.9 1612.74  4349.8 1610.32  4449.9 1609.23  4519.9 1607.11
  4539.9 1605.98  4649.9 1605.36  4657.7 1604.80  4658.0 1604.30  4661.8 1604.30
  4662.1 1604.80  4669.9 1605.34  4750.0 1604.92  4790.0 1605.91  4840.0 1605.62
  4970.1 1607.92  4980.1 1606.33  4990.1 1607.93  5060.6 1607.00  5141.3 1607.01
  5333.1 1609.43  5353.2 1609.41  5379.7 1608.36  5417.7 1609.72  5444.1 1611.09
  5544.1 1614.29  5615.6 1615.89  5645.9 1615.59  5746.8 1618.70  5762.1 1618.57
#Mann=6,-1,0
  4124.9    0.07       0  4250.9   0.035       0  4657.7   0.035       0
  4662.1   0.035       0  5379.7    0.07       0  5417.7   0.035       0
Bank Sta=4657.7,4662.1
Exp/Cntr=0.3,0.1

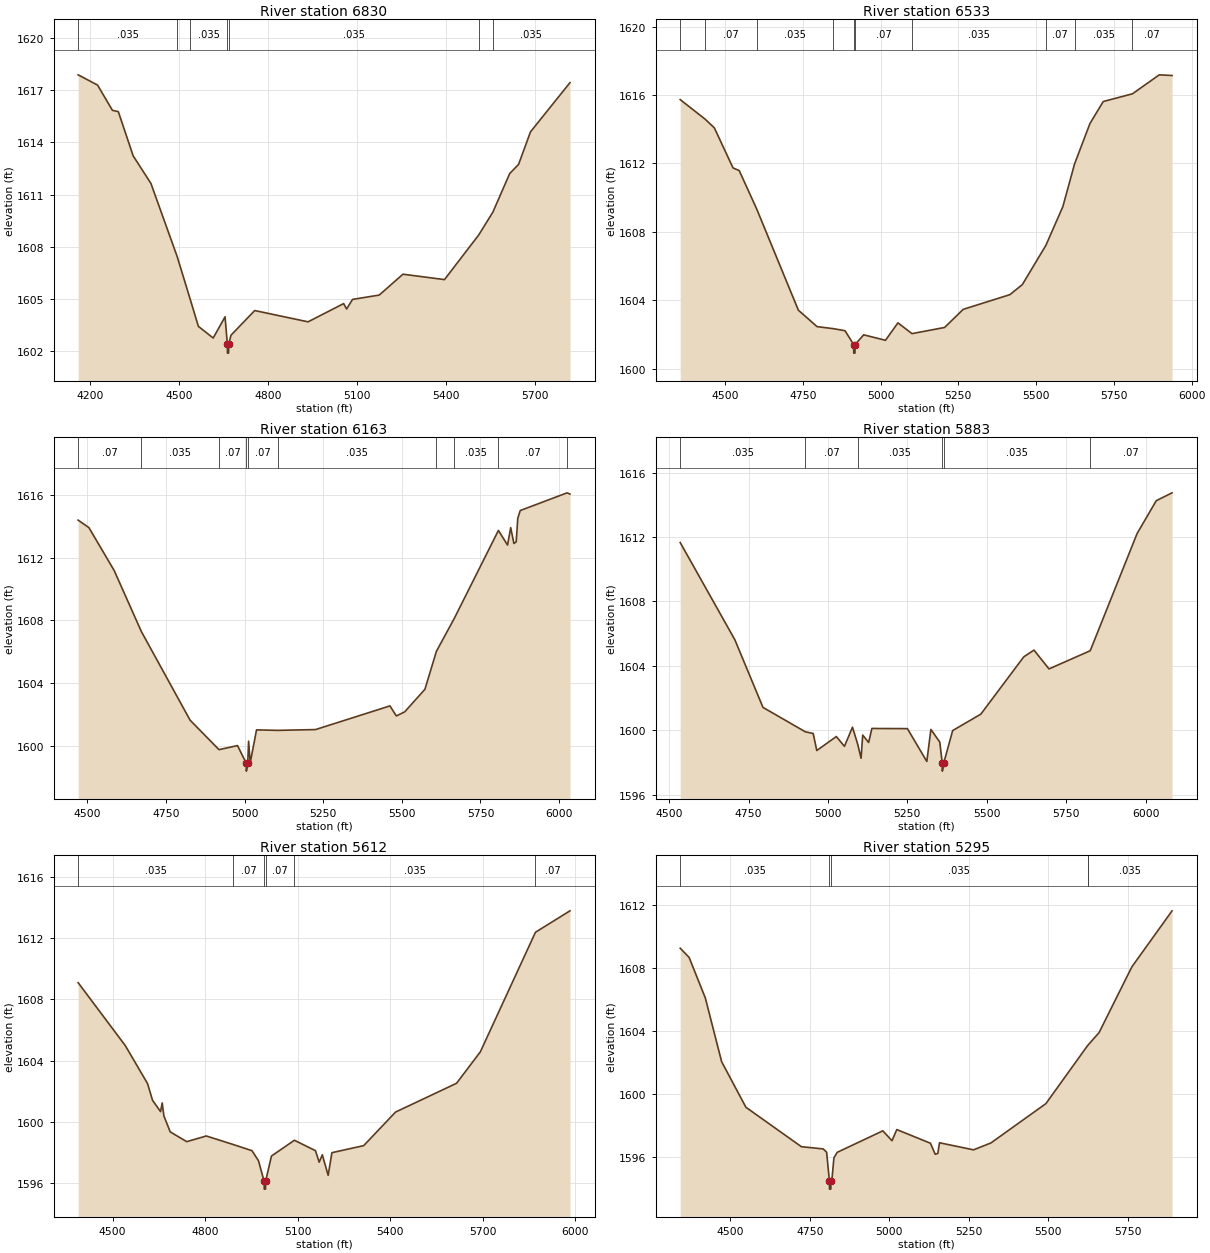
Type RM Length L Ch R = 1,6830,297,297,297
BEGIN DESCRIPTION:
Mapping XS c8e2d7d3
END DESCRIPTION:
XS GIS Cut Line= 3
      1593109.43      6959148.43      1593950.52      6959143.22
      1594768.21      6959161.45
#Sta/Elev= 30
  4159.8 1617.89  4225.4 1617.30  4275.4 1615.85  4295.4 1615.77  4345.4 1613.23
  4405.4 1611.64  4494.0 1607.43  4538.5 1604.94  4565.4 1603.42  4615.4 1602.75
  4655.4 1603.97  4663.2 1602.38  4663.5 1601.88  4667.3 1601.88  4667.6 1602.38
  4675.4 1602.91  4755.4 1604.33  4935.4 1603.68  5055.4 1604.73  5065.4 1604.42
  5085.4 1604.97  5175.4 1605.22  5255.5 1606.42  5395.5 1606.11  5511.1 1608.68
  5558.7 1609.99  5615.5 1612.21  5645.5 1612.74  5685.6 1614.61  5818.8 1617.44
#Mann=7,-1,0
  4159.8   0.035       0  4494.0    0.07       0  4538.5   0.035       0
  4663.2   0.035       0  4667.6   0.035       0  5511.1    0.07       0
  5558.7   0.035       0
Bank Sta=4663.2,4667.6
Exp/Cntr=0.3,0.1

Type RM Length L Ch R = 1,6533,370,370,370
BEGIN DESCRIPTION:
Mapping XS c17cb370
END DESCRIPTION:
XS GIS Cut Line= 3
      1593195.32      6959416.66      1593843.75      6959403.64
      1594776.10      6959416.66
#Sta/Elev= 30
  4356.0 1615.73  4436.0 1614.59  4465.7 1614.08  4525.7 1611.74  4545.7 1611.58
  4601.8 1609.34  4735.8 1603.42  4795.8 1602.46  4848.3 1602.34  4885.8 1602.22
  4913.5 1601.41  4913.8 1600.91  4917.7 1600.91  4918.1 1601.41  4945.8 1601.98
  5015.8 1601.66  5055.8 1602.68  5101.0 1602.05  5205.8 1602.41  5265.8 1603.47
  5415.9 1604.33  5455.9 1604.92  5531.4 1607.21  5585.9 1609.47  5623.6 1611.97
  5673.0 1614.33  5715.9 1615.62  5809.7 1616.07  5895.9 1617.18  5937.0 1617.14
#Mann=10,-1,0
  4356.0   0.035       0  4436.0    0.07       0  4601.8   0.035       0
  4848.3    0.07       0  4913.5    0.07       0  4918.1    0.07       0
  5101.0   0.035       0  5531.4    0.07       0  5623.6   0.035       0
  5809.7    0.07       0
Bank Sta=4913.5,4918.1
Exp/Cntr=0.3,0.1

Type RM Length L Ch R = 1,6163,280,280,280
BEGIN DESCRIPTION:
Mapping XS d1238eef
END DESCRIPTION:
XS GIS Cut Line= 3
      1593270.87      6959736.96      1593796.88      6959684.89
      1594821.50      6959539.25
#Sta/Elev= 30
  4471.1 1614.39  4505.4 1613.91  4585.8 1611.17  4672.2 1607.28  4827.0 1601.63
  4918.9 1599.75  4977.7 1600.01  5005.6 1598.88  5005.9 1598.38  5010.2 1598.88
  5013.0 1600.29  5018.1 1598.90  5038.2 1601.01  5106.0 1600.98  5225.7 1601.03
  5462.4 1602.54  5482.6 1601.90  5509.2 1602.16  5573.5 1603.60  5610.0 1606.02
  5667.1 1608.13  5807.1 1613.73  5836.1 1612.80  5846.2 1613.91  5856.3 1612.90
  5863.6 1613.00  5868.7 1614.51  5876.5 1615.00  6025.5 1616.13  6034.6 1616.05
#Mann=10,-1,0
  4471.1    0.07       0  4672.2   0.035       0  4918.9    0.07       0
  5005.6    0.07       0  5010.2    0.07       0  5106.0   0.035       0
  5610.0    0.07       0  5667.1   0.035       0  5807.1    0.07       0
  6025.5   0.035       0
Bank Sta=5005.6,5010.2
Exp/Cntr=0.3,0.1

Type RM Length L Ch R = 1,5883,271,271,271
BEGIN DESCRIPTION:
Mapping XS f8e543d0
END DESCRIPTION:
XS GIS Cut Line= 3
      1593388.29      6960037.76      1593836.23      6959923.17
      1594903.94      6959721.78
#Sta/Elev= 30
  4534.7 1611.66  4706.8 1605.62  4795.3 1601.42  4929.0 1599.90  4953.4 1599.80
  4964.8 1598.74  5026.3 1599.61  5051.9 1599.00  5077.2 1600.19  5093.1 1599.17
  5104.3 1598.26  5109.4 1599.70  5128.1 1599.24  5138.3 1600.11  5250.2 1600.10
  5311.3 1598.06  5324.1 1600.05  5352.0 1599.27  5359.9 1597.96  5360.2 1597.46
  5364.5 1597.96  5392.7 1599.98  5481.4 1601.00  5616.6 1604.56  5648.8 1604.98
  5696.1 1603.81  5825.9 1604.94  5973.5 1612.22  6033.8 1614.26  6083.6 1614.75
#Mann=6,-1,0
  4534.7   0.035       0  4929.0    0.07       0  5093.1   0.035       0
  5359.9    0.07       0  5364.5   0.035       0  5825.9    0.07       0
Bank Sta=5359.9,5364.5
Exp/Cntr=0.3,0.1

Type RM Length L Ch R = 1,5612,317,317,317
BEGIN DESCRIPTION:
Mapping XS edcbf449
END DESCRIPTION:
XS GIS Cut Line= 3
      1593442.17      6960301.63      1594021.99      6960101.99
      1594973.36      6959862.41
#Sta/Elev= 30
  4388.4 1609.09  4541.3 1604.98  4613.5 1602.50  4629.6 1601.41  4655.6 1600.67
  4660.9 1601.24  4666.4 1600.39  4686.8 1599.35  4740.4 1598.71  4803.9 1599.08
  4890.0 1598.53  4951.9 1598.12  4973.1 1597.46  4991.4 1596.11  4991.7 1595.61
  4995.7 1595.61  4996.0 1596.11  5015.0 1597.77  5089.4 1598.80  5157.8 1598.12
  5169.7 1597.37  5180.0 1597.85  5198.9 1596.51  5211.0 1597.99  5314.1 1598.45
  5417.2 1600.64  5615.0 1602.52  5692.1 1604.57  5870.8 1612.38  5982.7 1613.78
#Mann=6,-1,0
  4388.4   0.035       0  4890.0    0.07       0  4991.4    0.07       0
  4996.0    0.07       0  5089.4   0.035       0  5870.8    0.07       0
Bank Sta=4991.4,4996
Exp/Cntr=0.3,0.1

Type RM Length L Ch R = 1,5295,340,340,340
BEGIN DESCRIPTION:
Mapping XS c6223d0f
END DESCRIPTION:
XS GIS Cut Line= 3
      1593577.88      6960636.37      1594169.91      6960358.58
      1594984.13      6959990.53
#Sta/Elev= 30
  4342.4 1609.28  4370.3 1608.70  4421.5 1606.11  4472.7 1602.06  4549.1 1599.16
  4723.7 1596.65  4792.1 1596.51  4803.1 1596.30  4811.9 1594.45  4812.2 1593.95
  4816.2 1593.95  4816.5 1594.45  4820.4 1594.70  4826.0 1595.94  4836.3 1596.29
  4979.9 1597.66  5008.7 1597.03  5023.9 1597.74  5129.7 1596.87  5144.6 1596.17
  5152.8 1596.22  5158.3 1596.90  5265.3 1596.45  5320.1 1596.89  5492.9 1599.39
  5624.4 1603.09  5624.9 1603.10  5660.2 1603.91  5763.6 1608.10  5889.9 1611.66
#Mann=5,-1,0
  4342.4   0.035       0  4811.9   0.035       0  4816.5   0.035       0
  5624.4    0.07       0  5624.9   0.035       0
Bank Sta=4811.9,4816.5
Exp/Cntr=0.3,0.1

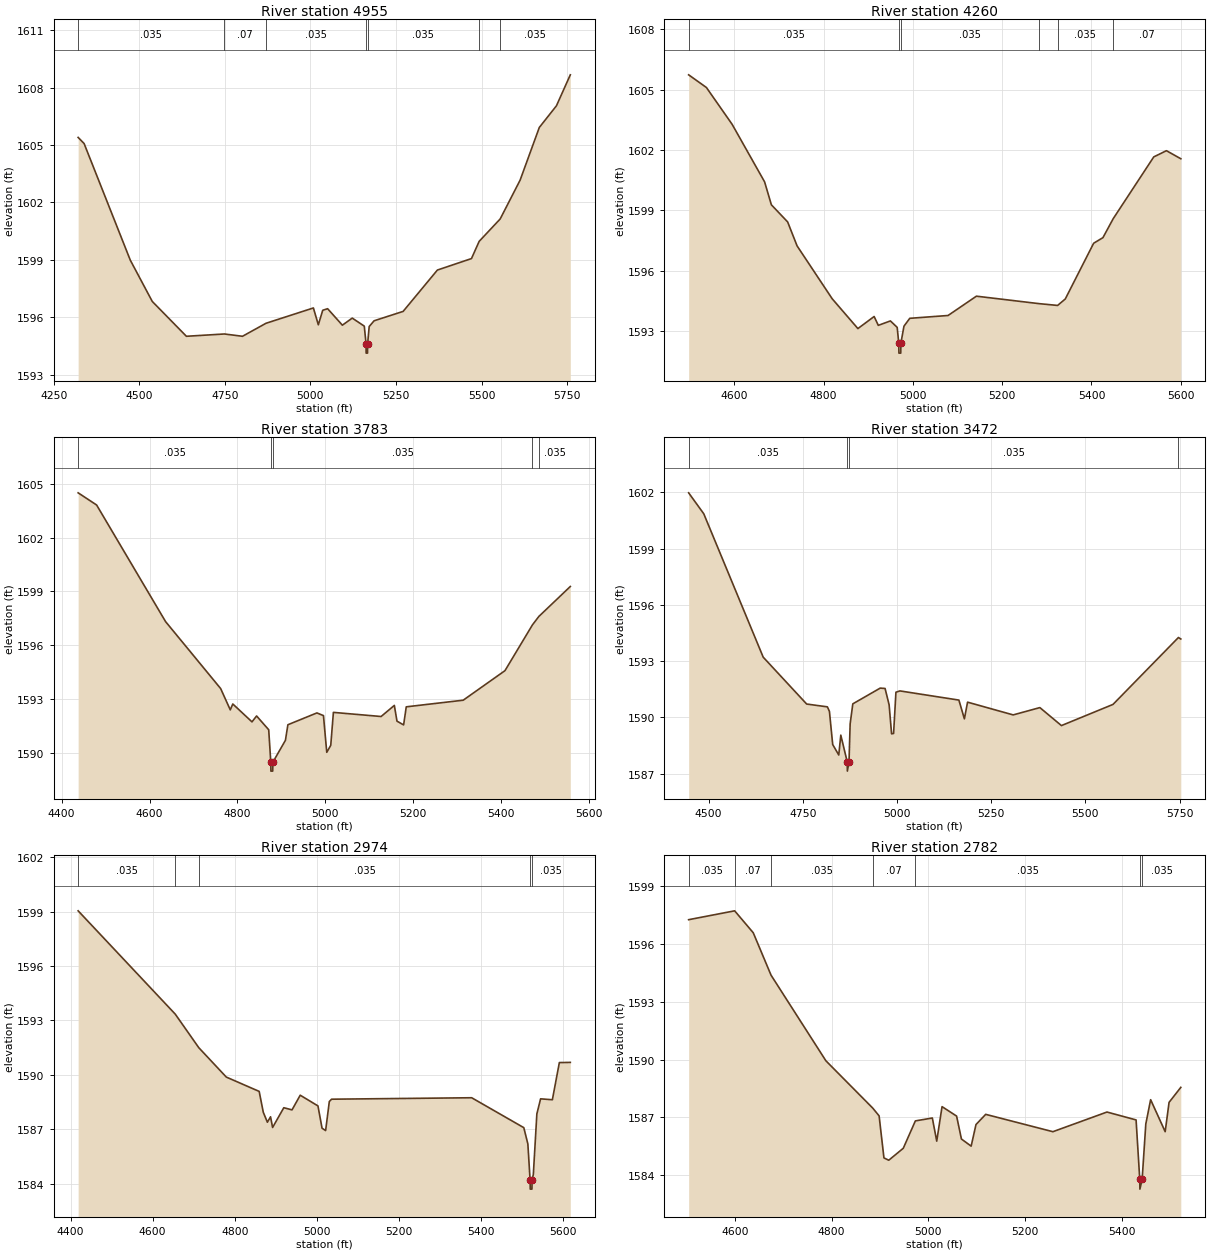
Type RM Length L Ch R = 1,4955,695,695,695
BEGIN DESCRIPTION:
Mapping XS 9f5ae38e
END DESCRIPTION:
XS GIS Cut Line= 3
      1593840.07      6960976.62      1594374.77      6960563.44
      1594966.50      6960082.77
#Sta/Elev= 30
  4321.3 1605.40  4338.7 1605.08  4473.6 1598.99  4537.9 1596.83  4637.6 1595.01
  4748.7 1595.13  4801.5 1595.01  4870.3 1595.69  5008.7 1596.49  5023.1 1595.61
  5036.0 1596.37  5050.3 1596.45  5093.4 1595.59  5122.2 1595.96  5157.4 1595.54
  5162.5 1594.63  5162.8 1594.13  5166.8 1594.13  5167.2 1594.63  5171.7 1595.52
  5186.1 1595.82  5270.9 1596.31  5371.0 1598.47  5470.6 1599.07  5493.1 1599.97
  5554.5 1601.14  5612.8 1603.17  5668.8 1605.92  5718.8 1607.05  5759.4 1608.67
#Mann=7,-1,0
  4321.3   0.035       0  4748.7    0.07       0  4870.3   0.035       0
  5162.5   0.035       0  5167.2   0.035       0  5493.1    0.07       0
  5554.5   0.035       0
Bank Sta=5162.5,5167.2
Exp/Cntr=0.3,0.1

Type RM Length L Ch R = 1,4260,477,477,477
BEGIN DESCRIPTION:
Mapping XS f04cee76
END DESCRIPTION:
XS GIS Cut Line= 3
      1594056.50      6961284.50      1594477.49      6961015.41
      1594926.70      6960613.95
#Sta/Elev= 30
  4498.0 1605.74  4537.8 1605.11  4595.4 1603.28  4668.1 1600.42  4683.3 1599.28
  4719.7 1598.43  4740.8 1597.24  4819.5 1594.61  4877.0 1593.13  4913.4 1593.73
  4922.7 1593.29  4949.8 1593.51  4965.0 1593.19  4968.5 1592.41  4968.9 1591.91
  4973.0 1591.91  4973.3 1592.41  4980.2 1593.25  4993.2 1593.64  5078.9 1593.78
  5142.4 1594.74  5282.2 1594.37  5324.2 1594.28  5341.4 1594.60  5404.9 1597.37
  5425.8 1597.65  5448.7 1598.59  5539.5 1601.66  5567.9 1601.97  5600.1 1601.57
#Mann=6,-1,0
  4498.0   0.035       0  4968.5   0.035       0  4973.3   0.035       0
  5282.2    0.07       0  5324.2   0.035       0  5448.7    0.07       0
Bank Sta=4968.5,4973.3
Exp/Cntr=0.3,0.1

Type RM Length L Ch R = 1,3783,311,311,311
BEGIN DESCRIPTION:
Mapping XS 83fa117f
END DESCRIPTION:
XS GIS Cut Line= 3
      1594168.10      6961609.47      1594658.52      6961342.56
      1594966.67      6960873.83
#Sta/Elev= 30
  4437.7 1604.50  4479.7 1603.82  4636.5 1597.31  4761.8 1593.57  4783.7 1592.38
  4789.4 1592.71  4833.1 1591.71  4843.5 1592.04  4871.1 1591.27  4875.8 1589.46
  4876.1 1588.96  4880.2 1588.96  4880.6 1589.46  4909.1 1590.68  4914.7 1591.55
  4980.7 1592.21  4995.6 1592.06  5003.1 1590.01  5012.2 1590.40  5018.2 1592.24
  5126.7 1592.01  5156.8 1592.63  5162.8 1591.75  5177.9 1591.54  5183.9 1592.55
  5313.4 1592.92  5408.4 1594.57  5471.0 1597.13  5485.6 1597.60  5557.0 1599.27
#Mann=5,-1,0
  4437.7   0.035       0  4875.8   0.035       0  4880.6   0.035       0
  5471.0    0.07       0  5485.6   0.035       0
Bank Sta=4875.8,4880.6
Exp/Cntr=0.3,0.1

Type RM Length L Ch R = 1,3472,498,498,498
BEGIN DESCRIPTION:
Mapping XS cf65eaa4
END DESCRIPTION:
XS GIS Cut Line= 3
      1594287.43      6961793.95      1594803.92      6961598.64
      1595409.38      6961149.42
#Sta/Elev= 30
  4447.3 1601.98  4487.5 1600.86  4645.2 1593.21  4760.5 1590.71  4815.5 1590.56
  4820.9 1590.32  4829.6 1588.55  4845.7 1587.99  4851.1 1589.05  4868.1 1587.63
  4868.5 1587.13  4872.9 1587.63  4875.9 1589.65  4883.0 1590.72  4955.7 1591.56
  4968.6 1591.54  4979.3 1590.67  4985.9 1589.12  4991.2 1589.14  4997.4 1591.34
  5008.0 1591.41  5164.5 1590.92  5179.1 1589.92  5187.5 1590.81  5308.5 1590.13
  5379.4 1590.52  5436.6 1589.56  5573.5 1590.69  5747.1 1594.26  5753.4 1594.18
#Mann=4,-1,0
  4447.3   0.035       0  4868.1   0.035       0  4872.9   0.035       0
  5747.1   0.063       0
Bank Sta=4868.1,4872.9
Exp/Cntr=0.3,0.1

Type RM Length L Ch R = 1,2974,192,192,192
BEGIN DESCRIPTION:
Mapping XS 1708ef10
END DESCRIPTION:
XS GIS Cut Line= 3
      1594374.18      6961937.18      1594955.83      6961956.71
      1595519.37      6961704.94
#Sta/Elev= 30
  4418.5 1599.04  4655.2 1593.34  4712.5 1591.49  4779.5 1589.87  4859.6 1589.08
  4869.6 1587.93  4879.6 1587.38  4887.3 1587.68  4892.3 1587.09  4919.6 1588.18
  4939.6 1588.06  4959.6 1588.87  5002.8 1588.28  5012.8 1587.05  5021.5 1586.92
  5030.5 1588.52  5036.0 1588.65  5377.4 1588.73  5504.4 1587.08  5514.3 1586.18
  5519.7 1584.19  5520.1 1583.69  5524.2 1583.69  5524.6 1584.19  5527.6 1584.50
  5536.2 1587.84  5545.3 1588.67  5574.0 1588.62  5591.0 1590.67  5617.7 1590.68
#Mann=5,-1,0
  4418.5   0.035       0  4655.2    0.07       0  4712.5   0.035       0
  5519.7   0.035       0  5524.6   0.035       0
Bank Sta=5519.7,5524.6
Exp/Cntr=0.3,0.1

Type RM Length L Ch R = 1,2782,422,422,422
BEGIN DESCRIPTION:
Mapping XS 53e1b3a7
END DESCRIPTION:
XS GIS Cut Line= 3
      1594501.44      6962157.71      1594996.71      6962134.79
      1595517.19      6962091.22
#Sta/Elev= 30
  4504.2 1597.26  4599.4 1597.72  4637.9 1596.58  4674.7 1594.38  4788.1 1589.94
  4885.2 1587.48  4898.2 1587.08  4908.2 1584.90  4918.2 1584.78  4948.2 1585.40
  4973.2 1586.82  5008.3 1586.97  5017.4 1585.77  5028.4 1587.56  5058.5 1587.07
  5068.5 1585.88  5088.6 1585.51  5098.6 1586.63  5118.7 1587.16  5257.7 1586.26
  5369.6 1587.28  5429.8 1586.87  5437.4 1583.78  5437.7 1583.28  5442.3 1583.78
  5449.9 1586.66  5459.9 1587.92  5490.0 1586.26  5498.0 1587.78  5522.3 1588.56
#Mann=7,-1,0
  4504.2   0.035       0  4599.4    0.07       0  4674.7   0.035       0
  4885.2    0.07       0  4973.2   0.035       0  5437.4   0.035       0
  5442.3   0.035       0
Bank Sta=5437.4,5442.3
Exp/Cntr=0.3,0.1

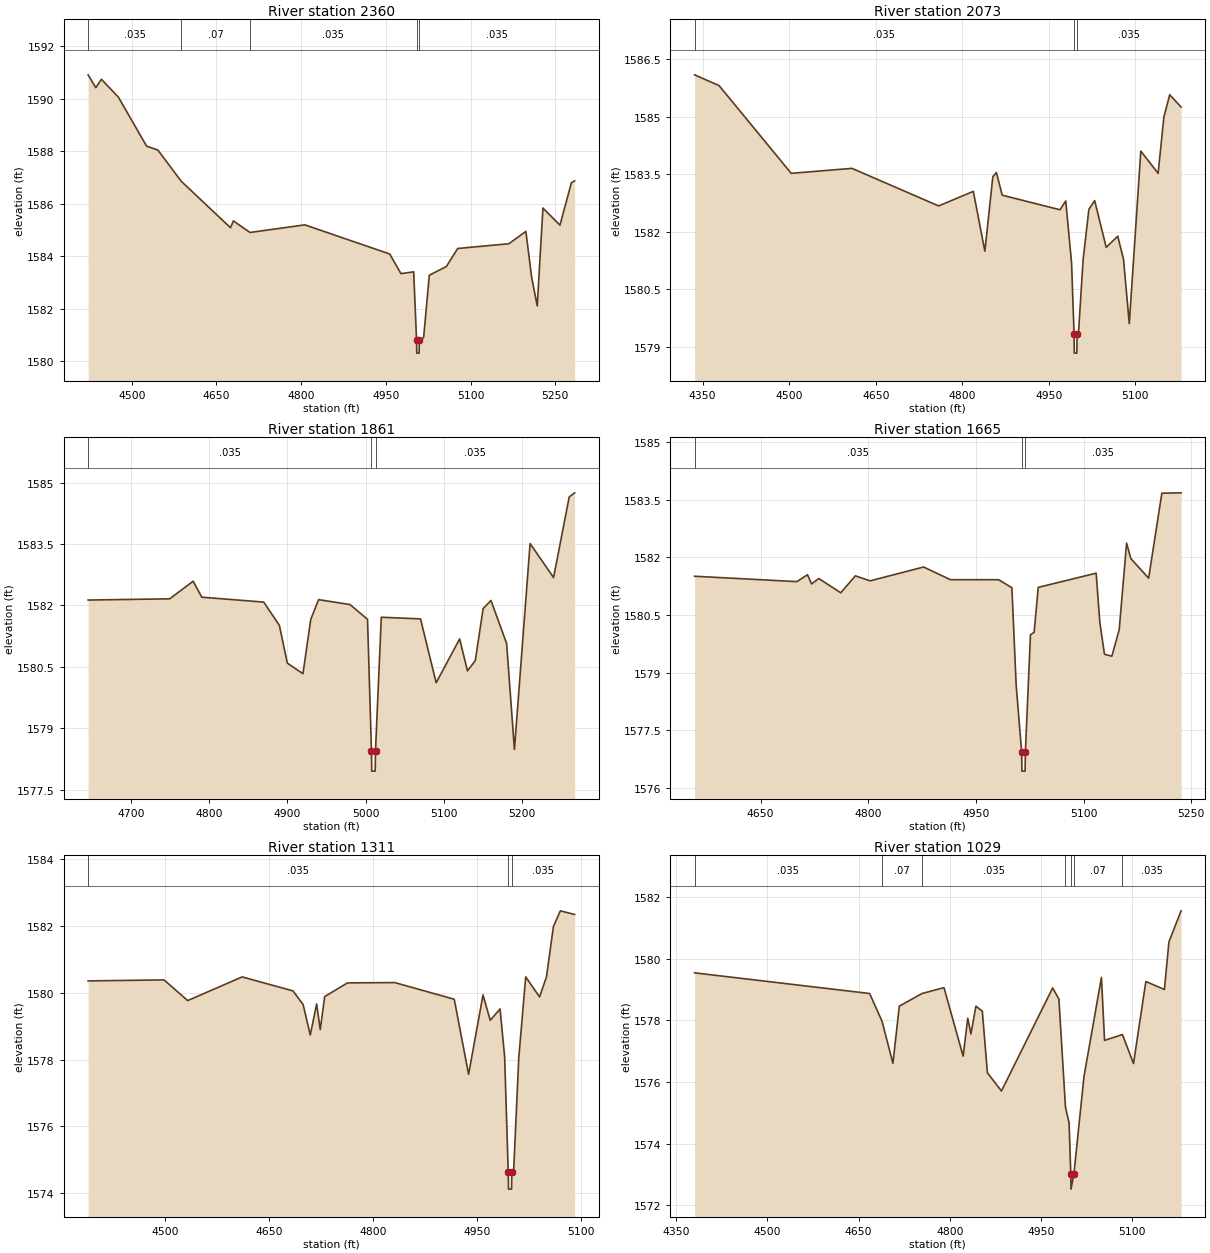
Type RM Length L Ch R = 1,2360,287,287,287
BEGIN DESCRIPTION:
Mapping XS 83e46968
END DESCRIPTION:
XS GIS Cut Line= 3
      1594651.44      6962432.79      1595227.53      6962410.70
      1595510.75      6962378.98
#Sta/Elev= 30
  4422.8 1590.91  4436.4 1590.42  4446.4 1590.74  4476.4 1590.06  4526.4 1588.19
  4546.4 1588.04  4587.8 1586.85  4675.0 1585.08  4680.0 1585.34  4709.5 1584.90
  4806.6 1585.19  4956.8 1584.08  4976.8 1583.33  4999.3 1583.40  5004.4 1580.80
  5004.7 1580.30  5008.9 1580.30  5009.3 1580.80  5016.9 1580.89  5027.0 1583.27
  5057.1 1583.60  5077.3 1584.29  5167.8 1584.47  5198.0 1584.94  5208.1 1583.20
  5218.1 1582.10  5228.2 1585.83  5258.4 1585.18  5278.5 1586.79  5284.3 1586.87
#Mann=5,-1,0
  4422.8   0.035       0  4587.8    0.07       0  4709.5   0.035       0
  5004.4   0.035       0  5009.3   0.035       0
Bank Sta=5004.4,5009.3
Exp/Cntr=0.3,0.1

Type RM Length L Ch R = 1,2073,212,212,212
BEGIN DESCRIPTION:
Mapping XS 5937784a
END DESCRIPTION:
XS GIS Cut Line= 3
      1594692.71      6962593.39      1595353.80      6962631.42
      1595534.74      6962625.94
#Sta/Elev= 30
  4336.1 1586.10  4378.5 1585.82  4503.6 1583.53  4608.8 1583.66  4759.1 1582.68
  4819.2 1583.06  4839.2 1581.50  4853.0 1583.44  4859.2 1583.55  4869.3 1582.96
  4969.4 1582.58  4979.4 1582.81  4989.5 1581.19  4993.8 1579.34  4994.2 1578.84
  4998.6 1578.84  4999.0 1579.34  5001.4 1579.34  5009.5 1581.28  5019.5 1582.59
  5029.5 1582.82  5049.5 1581.60  5069.5 1581.89  5079.5 1581.29  5089.5 1579.61
  5109.5 1584.11  5139.5 1583.53  5149.5 1585.00  5159.6 1585.58  5179.3 1585.26
#Mann=3,-1,0
  4336.1   0.035       0  4993.8   0.035       0  4999.0   0.035       0
Bank Sta=4993.8,4999
Exp/Cntr=0.3,0.1

Type RM Length L Ch R = 1,1861,196,196,196
BEGIN DESCRIPTION:
Mapping XS f68a1af7
END DESCRIPTION:
XS GIS Cut Line= 3
      1594901.03      6962784.36      1595254.75      6962806.06
      1595521.88      6962812.52
#Sta/Elev= 30
  4645.4 1582.13  4749.6 1582.16  4779.6 1582.59  4790.6 1582.20  4869.8 1582.08
  4889.8 1581.51  4899.9 1580.59  4919.9 1580.33  4929.9 1581.66  4939.9 1582.14
  4980.0 1582.02  5002.4 1581.66  5007.4 1578.45  5007.8 1577.95  5012.2 1577.95
  5012.6 1578.45  5020.0 1581.71  5070.1 1581.67  5090.1 1580.11  5120.1 1581.18
  5130.1 1580.40  5140.1 1580.65  5150.1 1581.92  5160.1 1582.12  5180.1 1581.07
  5190.1 1578.48  5210.1 1583.51  5240.1 1582.68  5260.1 1584.65  5267.0 1584.75
#Mann=3,-1,0
  4645.4   0.035       0  5007.4   0.035       0  5012.6   0.035       0
Bank Sta=5007.4,5012.6
Exp/Cntr=0.3,0.1

Type RM Length L Ch R = 1,1665,354,354,354
BEGIN DESCRIPTION:
Mapping XS 470d6a0b
END DESCRIPTION:
XS GIS Cut Line= 3
      1594874.94      6962903.71      1595309.16      6962986.28
      1595539.05      6963038.27
#Sta/Elev= 30
  4558.0 1581.51  4700.6 1581.37  4715.3 1581.55  4720.9 1581.31  4731.1 1581.45
  4761.6 1581.08  4782.0 1581.52  4802.4 1581.39  4877.1 1581.75  4914.3 1581.42
  4981.5 1581.42  5000.0 1581.21  5006.0 1578.67  5013.6 1576.94  5014.0 1576.44
  5018.4 1576.44  5018.8 1576.94  5025.9 1579.99  5031.0 1580.05  5036.7 1581.22
  5117.4 1581.59  5122.5 1580.31  5129.0 1579.48  5139.3 1579.43  5149.5 1580.12
  5159.8 1582.37  5165.7 1581.97  5190.5 1581.46  5208.9 1583.67  5235.7 1583.68
#Mann=3,-1,0
  4558.0   0.035       0  5013.6   0.035       0  5018.8   0.035       0
Bank Sta=5013.6,5018.8
Exp/Cntr=0.3,0.1

Type RM Length L Ch R = 1,1311,282,282,282
BEGIN DESCRIPTION:
Mapping XS a57288d0
END DESCRIPTION:
XS GIS Cut Line= 3
      1594866.27      6963122.89      1595455.16      6963288.00
      1595545.56      6963292.17
#Sta/Elev= 30
  4388.4 1580.36  4498.0 1580.39  4532.1 1579.77  4610.7 1580.48  4684.1 1580.06
  4698.7 1579.65  4709.0 1578.74  4718.2 1579.67  4723.4 1578.90  4729.8 1579.89
  4762.7 1580.30  4830.9 1580.31  4916.8 1579.81  4937.5 1577.56  4958.3 1579.94
  4968.7 1579.18  4982.9 1579.52  4989.5 1578.09  4994.7 1574.62  4995.1 1574.12
  4999.5 1574.12  4999.9 1574.62  5002.4 1574.62  5009.9 1578.05  5019.9 1580.48
  5039.9 1579.88  5049.9 1580.48  5059.9 1581.99  5069.9 1582.46  5090.5 1582.35
#Mann=3,-1,0
  4388.4   0.035       0  4994.7   0.035       0  4999.9   0.035       0
Bank Sta=4994.7,4999.9
Exp/Cntr=0.3,0.1

Type RM Length L Ch R = 1,1029,935,935,935
BEGIN DESCRIPTION:
Mapping XS be2e335d
END DESCRIPTION:
XS GIS Cut Line= 3
      1594764.27      6963346.41      1595352.09      6963533.06
      1595531.90      6963499.78
#Sta/Elev= 30
  4380.4 1579.54  4668.1 1578.87  4688.5 1577.97  4706.4 1576.61  4716.9 1578.46
  4754.2 1578.87  4790.3 1579.06  4821.8 1576.84  4829.4 1578.07  4834.6 1577.56
  4842.8 1578.46  4853.3 1578.30  4861.7 1576.30  4884.8 1575.71  4968.9 1579.05
  4979.2 1578.69  4990.0 1575.18  4995.9 1574.68  4998.7 1573.03  4999.1 1572.53
  5003.9 1573.03  5020.4 1576.18  5049.1 1579.39  5054.2 1577.35  5083.6 1577.54
  5101.8 1576.60  5122.1 1579.26  5152.6 1579.00  5160.0 1580.54  5180.0 1581.55
#Mann=7,-1,0
  4380.4   0.035       0  4688.5    0.07       0  4754.2   0.035       0
  4990.0    0.07       0  4998.7    0.07       0  5003.9    0.07       0
  5083.6   0.035       0
Bank Sta=4998.7,5003.9
Exp/Cntr=0.3,0.1

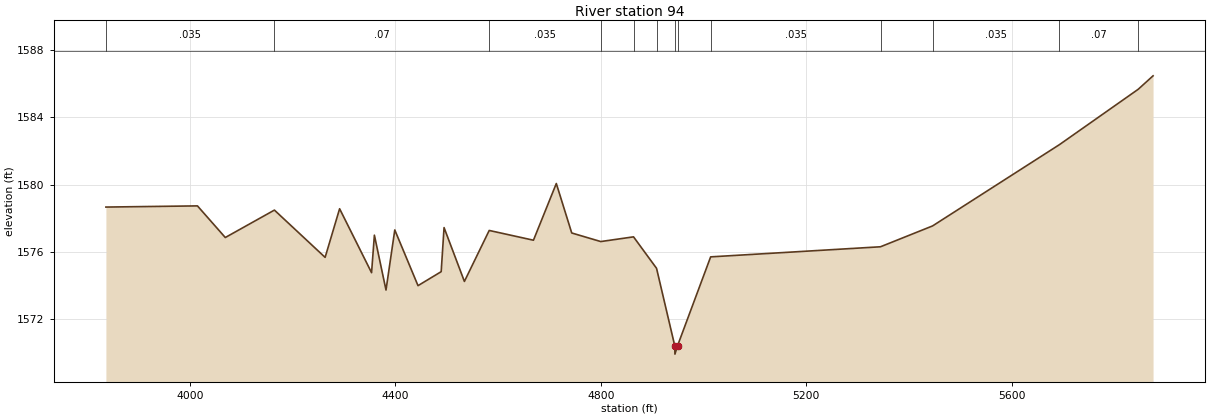
Type RM Length L Ch R = 1,94,0,0,0
BEGIN DESCRIPTION:
Mapping XS 83bc36fb
END DESCRIPTION:
XS GIS Cut Line= 3
      1594755.79      6963537.25      1595803.13      6964043.77
      1596364.29      6963372.67
#Sta/Elev= 30
  3836.6 1578.67  4014.8 1578.74  4069.0 1576.86  4164.6 1578.49  4263.3 1575.68
  4291.5 1578.57  4353.7 1574.77  4359.2 1577.00  4381.8 1573.74  4398.9 1577.31
  4444.1 1574.00  4489.2 1574.83  4494.8 1577.45  4534.4 1574.25  4582.7 1577.28
  4668.8 1576.70  4713.3 1580.07  4743.3 1577.13  4799.8 1576.62  4863.6 1576.90
  4908.4 1575.03  4943.8 1570.43  4944.2 1569.93  4949.3 1570.43  5013.7 1575.71
  5344.3 1576.31  5445.7 1577.55  5692.6 1582.38  5845.9 1585.67  5874.8 1586.47
#Mann=13,-1,0
  3836.6   0.035       0  4164.6    0.07       0  4582.7   0.035       0
  4799.8    0.07       0  4863.6   0.035       0  4908.4    0.16       0
  4943.8    0.07       0  4949.3    0.16       0  5013.7   0.035       0
  5344.3    0.16       0  5445.7   0.035       0  5692.6    0.07       0
  5845.9   0.035       0
Bank Sta=4943.8,4949.3
Exp/Cntr=0.3,0.1

Chan Stop Cuts=-1