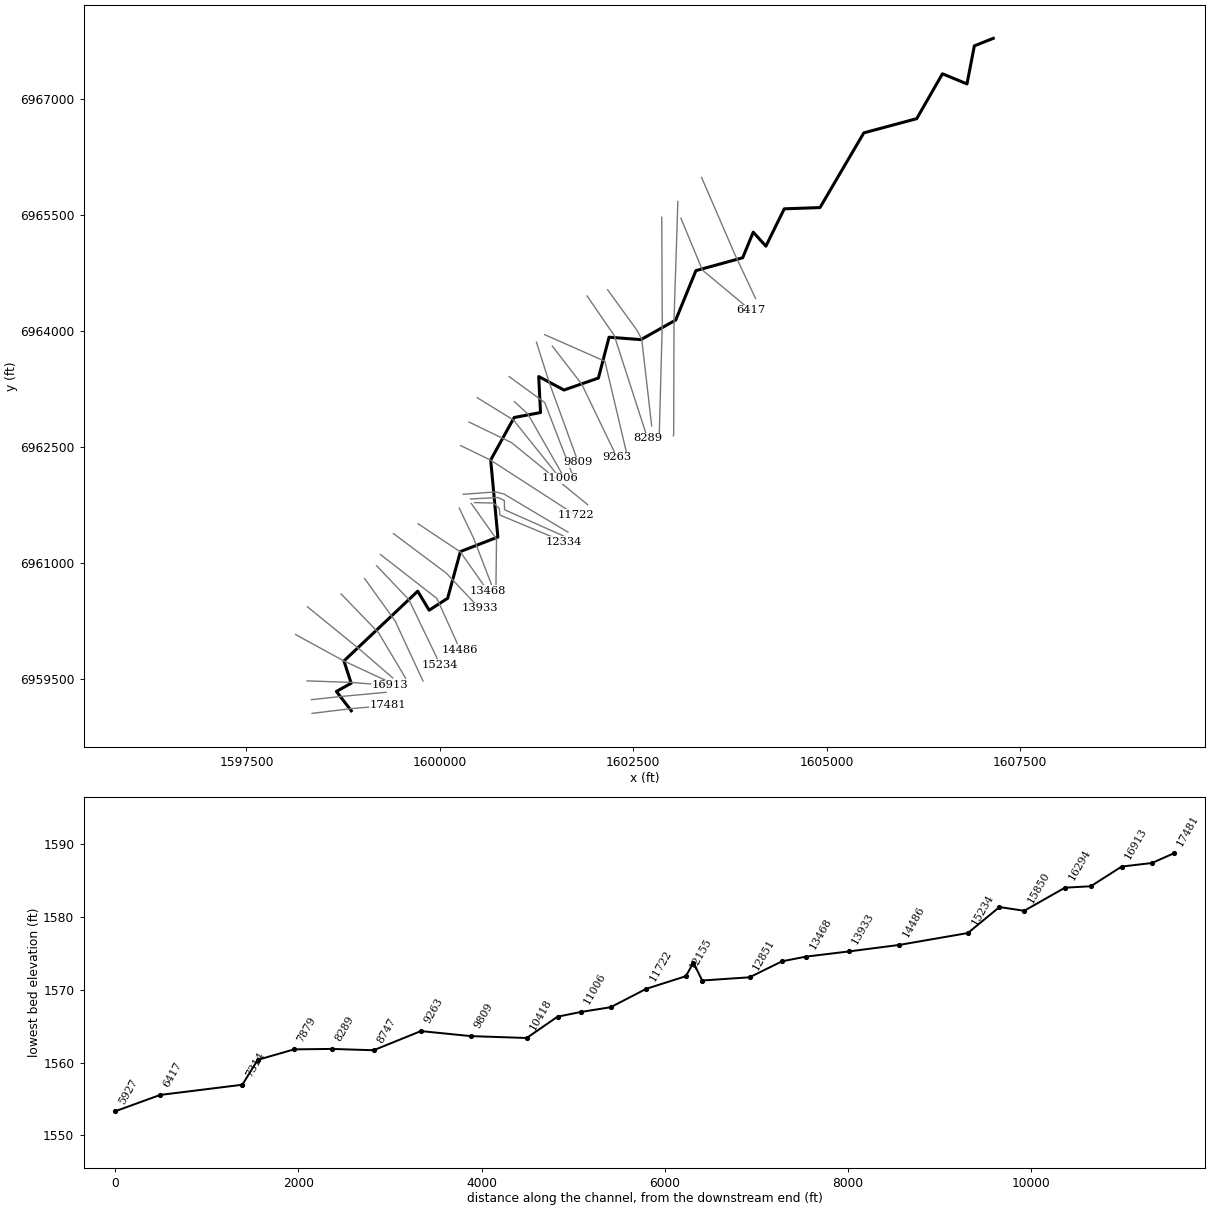
--- Chimney Creek 1118.prj (project) ---

Proj Title=Chimney Creek 1118 Base Level Engineering
Current Plan=p01
Default Exp/Contr=0.3,0.1
English Units
Geom File=g01
Flow File=f01
Plan File=p01
BEGIN DESCRIPTION:
Chimney Creek 1118
END DESCRIPTION:

--- Chimney Creek 1118.p01 (plan) ---

Plan Title=Multiple Run
Short Identifier=Multiple
Geom File=g01
Flow File=f01
Subcritical Flow
K Sum by GR= 0
Std Step Tol= 0.01
Critical Tol= 0.01
Num of Std Step Trials= 20
Max Error Tol= 0.3
Flow Tol Ratio= 0.001
Split Flow NTrial= 30
Split Flow Tol= 0.02
Split Flow Ratio= 0.02
Log Output Level= 0
Friction Slope Method= 1
Unsteady Friction Slope Method= 2
Unsteady Bridges Friction Slope Method= 1
Parabolic Critical Depth
Global Vel Dist=  1 , 1 , 1
Global Log Level= 0
CheckData=True
Encroach Param= -1, 0, 0, 0
BEGIN DESCRIPTION:
Multiple Run
END DESCRIPTION:

--- Chimney Creek 1118.f01 (steady flow) ---

Flow Title=Multiple
Number of Profiles=7
Profile Names=10-year,25-year,50-year,1pct_min,100-year,1pct_plu,500-year
River Rch & RM= Chimney Creek 11,Reach-1,17481
     206     279     339     205     409     816     602
River Rch & RM= Chimney Creek 11,Reach-1,15850
     277     380     464     281     562    1121     835
River Rch & RM= Chimney Creek 11,Reach-1,9263
     388     541     668     409     816    1629    1238
River Rch & RM= Chimney Creek 11,Reach-1,6417
     464     651     807     497     991    1978    1516
River Rch & RM= Chimney Creek 11,Reach-1,2943
     479     674     836     515    1027    2048    1570
River Rch & RM= Chimney Creek 11,Reach-1,1655
     524     738     917     566    1129    2252    1732
Boundary for River Rch & Prof#=Chimney Creek 11,Reach-1,1
Up Type=0
Dn Type=3
Dn Slope=0.005
Boundary for River Rch & Prof#=Chimney Creek 11,Reach-1,2
Up Type=0
Dn Type=3
Dn Slope=0.005
Boundary for River Rch & Prof#=Chimney Creek 11,Reach-1,3
Up Type=0
Dn Type=3
Dn Slope=0.005
Boundary for River Rch & Prof#=Chimney Creek 11,Reach-1,4
Up Type=0
Dn Type=3
Dn Slope=0.005
Boundary for River Rch & Prof#=Chimney Creek 11,Reach-1,5
Up Type=0
Dn Type=3
Dn Slope=0.005
Boundary for River Rch & Prof#=Chimney Creek 11,Reach-1,6
Up Type=0
Dn Type=3
Dn Slope=0.005
Boundary for River Rch & Prof#=Chimney Creek 11,Reach-1,7
Up Type=0
Dn Type=3
Dn Slope=0.005

--- Chimney Creek 1118.g01 (geometry) ---

Geom Title=Existing Conditions

River Reach=Chimney Creek 11,Reach-1
Reach XY= 30
      1598855.00      6959088.00      1598662.18      6959338.33
      1598853.52      6959443.88      1598760.03      6959732.92
      1599713.71      6960635.08      1599861.51      6960389.38
      1600100.37      6960543.19      1600265.46      6961147.82
      1600749.92      6961335.68      1600657.06      6962332.14
      1600960.59      6962882.45      1601301.49      6962946.43
      1601278.00      6963412.47      1601605.00      6963238.00
      1602049.99      6963393.00      1602187.47      6963921.36
      1602599.72      6963889.99      1603049.42      6964143.58
      1603310.44      6964782.75      1603915.08      6964949.10
      1604051.60      6965280.59      1604214.99      6965098.95
      1604452.63      6965582.24      1604914.83      6965598.43
      1605481.42      6966565.16      1606164.81      6966748.51
      1606498.01      6967329.17      1606815.16      6967198.28
      1606910.34      6967690.74      1607155.00      6967788.00

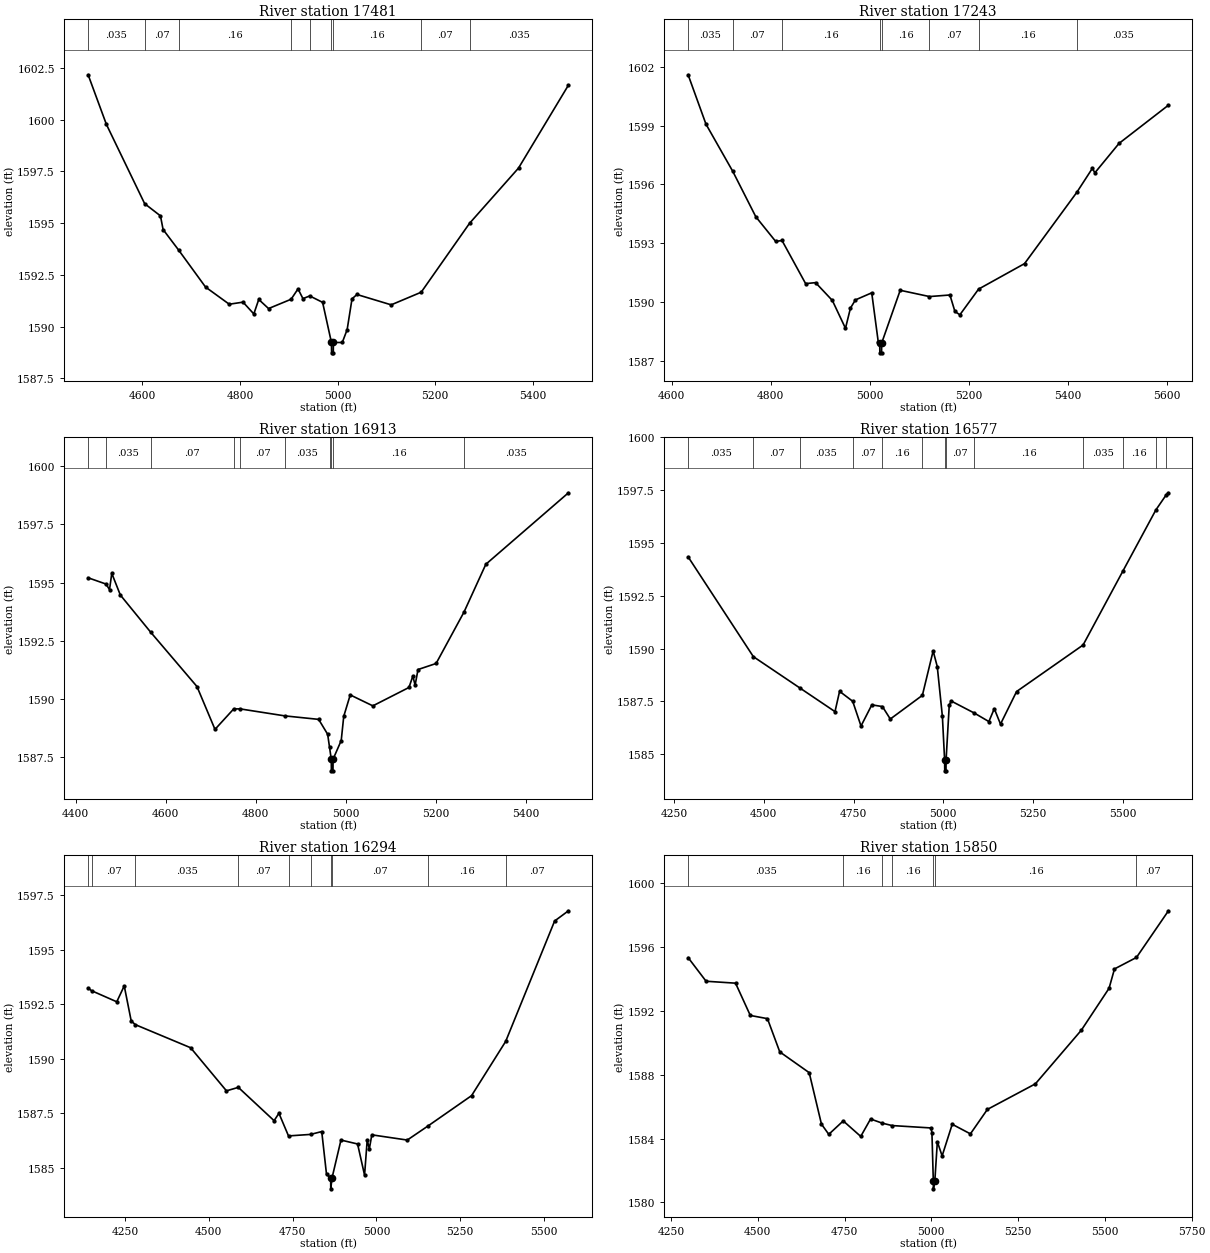
Type RM Length L Ch R = 1,17481,238,238,238
BEGIN DESCRIPTION:
Chimney Creek 1118 24.0
END DESCRIPTION:
XS GIS Cut Line= 3
      1598347.78      6959054.49      1598855.38      6959115.89
      1599327.00      6959156.92
#Sta/Elev= 30
  4488.7 1602.17  4526.2 1599.77  4604.6 1595.94  4637.0 1595.35  4642.4 1594.69
  4674.8 1593.68  4729.4 1591.91  4778.0 1591.08  4806.3 1591.18  4828.4 1590.61
  4838.5 1591.31  4858.6 1590.87  4904.8 1591.32  4919.0 1591.82  4929.1 1591.35
  4943.0 1591.48  4969.4 1591.17  4987.5 1589.23  4987.8 1588.73  4991.3 1588.73
  4991.5 1589.23  5009.7 1589.23  5019.7 1589.85  5029.7 1591.34  5039.8 1591.55
  5110.0 1591.05  5171.5 1591.66  5270.6 1594.99  5371.0 1597.66  5473.4 1601.67
#Mann=9,-1,0
  4488.7   0.035       0  4604.6    0.07       0  4674.8    0.16       0
  4904.8    0.07       0  4943.0    0.16       0  4987.5    0.07       0
  4991.5    0.16       0  5171.5    0.07       0  5270.6   0.035       0
Bank Sta=4987.5,4991.5
Exp/Cntr=0.3,0.1

Type RM Length L Ch R = 1,17243,330,330,330
BEGIN DESCRIPTION:
Mapping XS cd4fdad1
END DESCRIPTION:
XS GIS Cut Line= 3
      1598339.12      6959231.57      1598705.46      6959271.51
      1599304.38      6959327.06
#Sta/Elev= 30
  4633.0 1601.59  4669.1 1599.07  4723.3 1596.66  4769.7 1594.35  4809.9 1593.09
  4822.6 1593.14  4870.3 1590.94  4890.4 1590.99  4924.3 1590.08  4950.8 1588.66
  4960.8 1589.69  4970.9 1590.11  5003.8 1590.47  5016.9 1587.98  5019.9 1587.91
  5020.2 1587.41  5023.7 1587.41  5023.9 1587.91  5061.3 1590.60  5120.4 1590.28
  5161.7 1590.36  5171.8 1589.52  5181.8 1589.35  5219.6 1590.66  5312.4 1591.96
  5418.1 1595.60  5449.4 1596.82  5454.4 1596.59  5503.2 1598.09  5603.0 1600.04
#Mann=8,-1,0
  4633.0   0.035       0  4723.3    0.07       0  4822.6    0.16       0
  5019.9    0.07       0  5023.9    0.16       0  5120.4    0.07       0
  5219.6    0.16       0  5418.1   0.035       0
Bank Sta=5019.9,5023.9
Exp/Cntr=0.3,0.1

Type RM Length L Ch R = 1,16913,336,336,336
BEGIN DESCRIPTION:
Mapping XS a97de328
END DESCRIPTION:
XS GIS Cut Line= 3
      1598283.56      6959474.63      1598851.30      6959455.53
      1599347.84      6959415.60
#Sta/Elev= 30
  4427.9 1595.21  4467.7 1594.94  4475.4 1594.70  4480.4 1595.40  4499.4 1594.47
  4566.9 1592.87  4669.5 1590.54  4709.5 1588.70  4751.1 1589.58  4765.3 1589.58
  4864.5 1589.28  4939.6 1589.13  4959.6 1588.49  4963.7 1587.94  4967.6 1587.42
  4967.9 1586.92  4971.4 1586.92  4971.6 1587.42  4989.7 1588.22  4995.3 1589.26
  5009.7 1590.18  5059.9 1589.71  5140.1 1590.50  5148.7 1590.99  5153.7 1590.60
  5160.2 1591.27  5200.3 1591.53  5262.3 1593.74  5310.7 1595.79  5494.1 1598.86
#Mann=10,-1,0
  4427.9    0.07       0  4467.7   0.035       0  4566.9    0.07       0
  4751.1   0.035       0  4765.3    0.07       0  4864.5   0.035       0
  4963.7    0.16       0  4967.6    0.07       0  4971.6    0.16       0
  5262.3   0.035       0
Bank Sta=4967.6,4971.6
Exp/Cntr=0.3,0.1

Type RM Length L Ch R = 1,16577,283,283,283
BEGIN DESCRIPTION:
Mapping XS 641f7884
END DESCRIPTION:
XS GIS Cut Line= 3
      1598135.99      6960073.61      1598757.55      6959733.31
      1599328.69      6959467.70
#Sta/Elev= 30
  4289.1 1594.34  4470.9 1589.62  4601.3 1588.13  4698.4 1587.02  4711.2 1587.98
  4747.7 1587.51  4770.9 1586.34  4801.0 1587.34  4830.6 1587.26  4852.5 1586.67
  4941.9 1587.79  4971.9 1589.89  4983.4 1589.15  4997.7 1586.79  5003.9 1584.72
  5004.2 1584.22  5007.7 1584.22  5007.9 1584.72  5016.8 1587.33  5022.3 1587.52
  5086.9 1586.95  5127.2 1586.55  5142.3 1587.16  5159.6 1586.43  5204.4 1587.97
  5389.7 1590.17  5500.4 1593.66  5592.6 1596.56  5620.9 1597.26  5627.6 1597.37
#Mann=13,-1,0
  4289.1   0.035       0  4470.9    0.07       0  4601.3   0.035       0
  4747.7    0.07       0  4830.6    0.16       0  4941.9    0.07       0
  5003.9    0.07       0  5007.9    0.07       0  5086.9    0.16       0
  5389.7   0.035       0  5500.4    0.16       0  5592.6   0.035       0
  5620.9    0.07       0
Bank Sta=5003.9,5007.9
Exp/Cntr=0.3,0.1

Type RM Length L Ch R = 1,16294,444,444,444
BEGIN DESCRIPTION:
Mapping XS b55f2160
END DESCRIPTION:
XS GIS Cut Line= 3
      1598288.78      6960432.98      1598957.20      6959887.83
      1599389.50      6959514.55
#Sta/Elev= 30
  4139.6 1593.24  4149.8 1593.12  4225.1 1592.61  4247.4 1593.34  4268.2 1591.73
  4280.6 1591.56  4445.5 1590.50  4552.5 1588.52  4587.9 1588.68  4694.7 1587.15
  4709.1 1587.49  4737.7 1586.45  4803.7 1586.52  4836.9 1586.65  4851.2 1584.68
  4863.6 1584.52  4863.8 1584.02  4867.6 1584.52  4894.3 1586.26  4943.9 1586.08
  4964.7 1584.65  4972.6 1586.26  4979.0 1585.86  4986.4 1586.50  5092.2 1586.26
  5153.4 1586.90  5284.1 1588.30  5385.9 1590.79  5532.0 1596.32  5573.3 1596.79
#Mann=10,-1,0
  4139.6   0.035       0  4149.8    0.07       0  4280.6   0.035       0
  4587.9    0.07       0  4737.7   0.035       0  4803.7    0.07       0
  4863.6    0.07       0  4867.6    0.07       0  5153.4    0.16       0
  5385.9    0.07       0
Bank Sta=4863.6,4867.6
Exp/Cntr=0.3,0.1

Type RM Length L Ch R = 1,15850,271,271,271
BEGIN DESCRIPTION:
Mapping XS f61003c6
END DESCRIPTION:
XS GIS Cut Line= 3
      1598723.19      6960599.44      1599207.55      6960097.72
      1599558.26      6959507.41
#Sta/Elev= 30
  4299.1 1595.32  4350.9 1593.84  4435.8 1593.72  4478.3 1591.70  4527.7 1591.50
  4563.2 1589.42  4648.0 1588.12  4683.3 1584.90  4704.4 1584.26  4746.1 1585.10
  4796.5 1584.13  4824.8 1585.22  4858.5 1584.96  4886.7 1584.81  4998.9 1584.66
  5001.6 1584.37  5005.6 1581.35  5005.9 1580.85  5010.0 1581.35  5017.2 1583.80
  5031.0 1582.91  5060.1 1584.89  5112.5 1584.29  5161.4 1585.82  5299.7 1587.42
  5432.2 1590.78  5512.0 1593.40  5527.6 1594.61  5591.0 1595.33  5683.1 1598.25
#Mann=7,-1,0
  4299.1   0.035       0  4746.1    0.16       0  4858.5    0.07       0
  4886.7    0.16       0  5005.6    0.07       0  5010.0    0.16       0
  5591.0    0.07       0
Bank Sta=5005.6,5010
Exp/Cntr=0.3,0.1

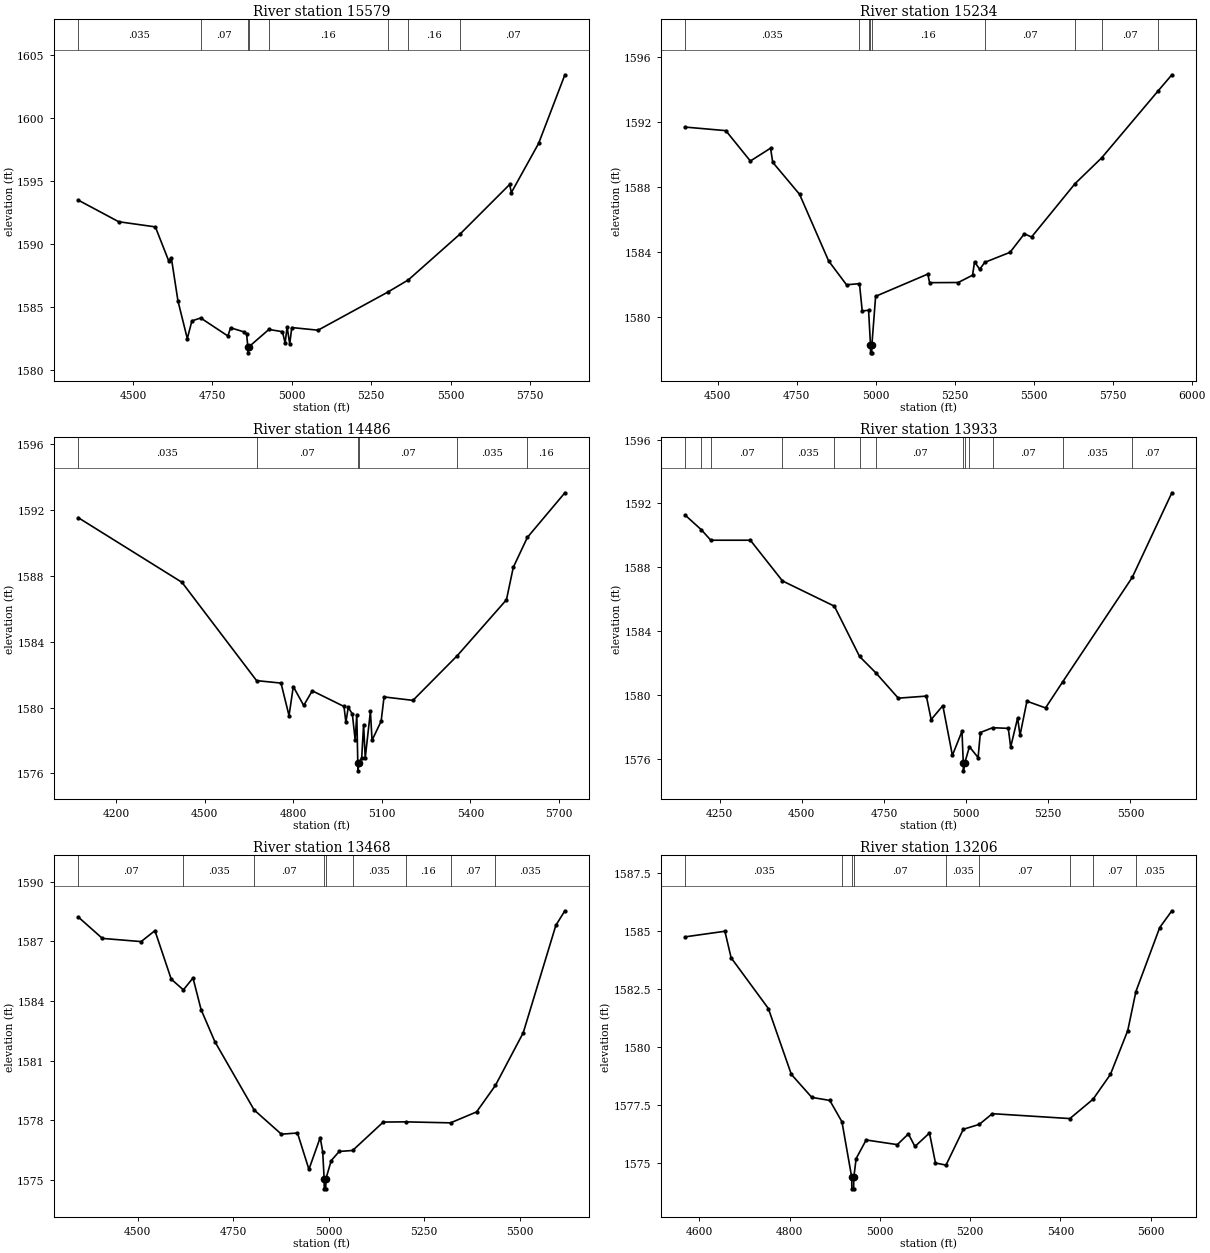
Type RM Length L Ch R = 1,15579,345,345,345
BEGIN DESCRIPTION:
Mapping XS af8f5269
END DESCRIPTION:
XS GIS Cut Line= 3
      1599026.98      6960798.69      1599421.96      6960249.63
      1599782.14      6959472.84
#Sta/Elev= 30
  4327.3 1593.50  4454.9 1591.78  4570.3 1591.37  4612.0 1588.69  4620.6 1588.91
  4641.5 1585.48  4670.9 1582.49  4685.4 1583.90  4713.1 1584.13  4798.6 1582.70
  4807.2 1583.35  4848.9 1583.03  4857.5 1582.87  4861.5 1581.86  4861.8 1581.36
  4865.9 1581.86  4927.9 1583.22  4970.5 1583.04  4979.0 1582.14  4985.2 1583.43
  4993.4 1582.06  4999.9 1583.37  5082.6 1583.16  5302.4 1586.19  5367.1 1587.16
  5531.0 1590.83  5685.9 1594.74  5691.4 1594.10  5777.1 1598.00  5859.9 1603.46
#Mann=8,-1,0
  4327.3   0.035       0  4713.1    0.07       0  4861.5    0.07       0
  4865.9    0.07       0  4927.9    0.16       0  5302.4    0.07       0
  5367.1    0.16       0  5531.0    0.07       0
Bank Sta=4861.5,4865.9
Exp/Cntr=0.3,0.1

Type RM Length L Ch R = 1,15234,748,748,748
BEGIN DESCRIPTION:
Mapping XS 8f0205e5
END DESCRIPTION:
XS GIS Cut Line= 3
      1599181.06      6960965.78      1599599.91      6960525.24
      1600003.56      6959685.38
#Sta/Elev= 30
  4397.7 1591.69  4526.3 1591.47  4603.9 1589.60  4667.8 1590.39  4674.7 1589.52
  4759.6 1587.55  4851.5 1583.45  4908.1 1581.98  4949.1 1582.05  4957.8 1580.37
  4977.9 1580.41  4983.9 1578.29  4984.2 1577.79  4988.1 1577.79  4988.4 1578.29
  5000.2 1581.27  5165.4 1582.64  5170.9 1582.11  5261.5 1582.12  5306.8 1582.57
  5313.2 1583.40  5329.4 1582.93  5345.4 1583.36  5425.5 1583.98  5470.8 1585.12
  5493.4 1584.92  5631.2 1588.21  5715.5 1589.80  5894.4 1593.93  5937.4 1594.91
#Mann=9,-1,0
  4397.7   0.035       0  4949.1    0.07       0  4977.9    0.16       0
  4983.9    0.07       0  4988.4    0.16       0  5345.4    0.07       0
  5631.2    0.16       0  5715.5    0.07       0  5894.4    0.16       0
Bank Sta=4983.9,4988.4
Exp/Cntr=0.3,0.1

Type RM Length L Ch R = 1,14486,553,553,553
BEGIN DESCRIPTION:
Mapping XS 634eea2f
END DESCRIPTION:
XS GIS Cut Line= 3
      1599232.87      6961109.44      1599962.03      6960540.86
      1600260.76      6959880.64
#Sta/Elev= 30
  4070.8 1591.54  4422.5 1587.61  4675.3 1581.64  4758.1 1581.49  4785.3 1579.51
  4799.7 1581.28  4835.0 1580.13  4864.0 1581.02  4971.6 1580.07  4977.9 1579.11
  4986.1 1580.02  4999.8 1579.61  5009.4 1578.04  5014.9 1579.58  5018.3 1576.66
  5018.6 1576.16  5022.8 1576.66  5031.5 1576.94  5038.0 1578.97  5043.5 1576.94
  5061.1 1579.77  5066.6 1578.02  5097.4 1579.17  5107.3 1580.65  5205.2 1580.44
  5355.6 1583.16  5522.1 1586.55  5545.2 1588.52  5593.0 1590.34  5720.1 1593.05
#Mann=6,-1,0
  4070.8   0.035       0  4675.3    0.07       0  5018.3    0.07       0
  5022.8    0.07       0  5355.6   0.035       0  5593.0    0.16       0
Bank Sta=5018.3,5022.8
Exp/Cntr=0.3,0.1

Type RM Length L Ch R = 1,13933,465,465,465
BEGIN DESCRIPTION:
Mapping XS 32f6f3f4
END DESCRIPTION:
XS GIS Cut Line= 3
      1599399.96      6961380.72      1600083.56      6960868.56
      1600513.15      6960412.92
#Sta/Elev= 30
  4145.5 1591.27  4194.4 1590.36  4223.4 1589.70  4343.7 1589.70  4441.5 1587.15
  4599.3 1585.57  4676.0 1582.42  4725.7 1581.39  4793.7 1579.81  4879.1 1579.94
  4893.7 1578.47  4929.2 1579.34  4958.3 1576.23  4987.5 1577.74  4991.4 1575.76
  4991.8 1575.26  4996.0 1575.76  5010.1 1576.77  5036.5 1576.09  5043.4 1577.66
  5080.7 1577.96  5128.3 1577.92  5135.6 1576.75  5156.7 1578.57  5164.0 1577.49
  5185.0 1579.62  5241.6 1579.20  5293.7 1580.83  5505.3 1587.37  5625.9 1592.67
#Mann=13,-1,0
  4145.5    0.07       0  4194.4   0.035       0  4223.4    0.07       0
  4441.5   0.035       0  4599.3    0.07       0  4676.0   0.035       0
  4725.7    0.07       0  4991.4    0.07       0  4996.0    0.07       0
  5010.1    0.16       0  5080.7    0.07       0  5293.7   0.035       0
  5505.3    0.07       0
Bank Sta=4991.4,4996
Exp/Cntr=0.3,0.1

Type RM Length L Ch R = 1,13468,262,262,262
BEGIN DESCRIPTION:
Mapping XS acd9b345
END DESCRIPTION:
XS GIS Cut Line= 3
      1599717.85      6961508.44      1600264.69      6961143.87
      1600618.86      6960638.67
#Sta/Elev= 30
  4344.5 1588.23  4407.8 1587.15  4509.3 1586.99  4545.4 1587.54  4588.1 1585.10
  4619.9 1584.56  4645.1 1585.16  4666.2 1583.57  4702.2 1581.96  4805.1 1578.52
  4876.5 1577.30  4918.6 1577.36  4948.6 1575.53  4978.1 1577.13  4984.7 1576.41
  4988.4 1575.05  4988.7 1574.55  4992.7 1574.55  4993.0 1575.05  5006.9 1575.97
  5027.8 1576.43  5063.0 1576.48  5143.2 1577.91  5202.1 1577.92  5319.4 1577.87
  5387.5 1578.42  5436.7 1579.75  5509.6 1582.40  5595.1 1587.81  5618.7 1588.54
#Mann=9,-1,0
  4344.5    0.07       0  4619.9   0.035       0  4805.1    0.07       0
  4988.4    0.07       0  4993.0    0.07       0  5063.0   0.035       0
  5202.1    0.16       0  5319.4    0.07       0  5436.7   0.035       0
Bank Sta=4988.4,4993
Exp/Cntr=0.3,0.1

Type RM Length L Ch R = 1,13206,355,355,355
BEGIN DESCRIPTION:
Mapping XS 6d2c9046
END DESCRIPTION:
XS GIS Cut Line= 3
      1600250.81      6961709.84      1600436.57      6961320.96
      1600669.22      6960716.77
#Sta/Elev= 30
  4568.7 1584.74  4656.7 1584.98  4670.5 1583.84  4753.0 1581.66  4803.9 1578.83
  4849.3 1577.84  4889.1 1577.71  4916.1 1576.79  4937.7 1574.41  4938.0 1573.91
  4942.0 1573.91  4942.4 1574.41  4947.5 1575.21  4969.7 1576.01  5038.7 1575.81
  5063.3 1576.27  5077.8 1575.73  5110.0 1576.31  5123.3 1575.02  5146.6 1574.93
  5185.0 1576.47  5220.3 1576.68  5249.3 1577.14  5421.1 1576.93  5472.4 1577.76
  5511.0 1578.83  5549.3 1580.71  5567.4 1582.39  5620.2 1585.14  5647.1 1585.86
#Mann=9,-1,0
  4568.7   0.035       0  4916.1    0.07       0  4937.7    0.07       0
  4942.4    0.07       0  5146.6   0.035       0  5220.3    0.07       0
  5421.1    0.16       0  5472.4    0.07       0  5567.4   0.035       0
Bank Sta=4937.7,4942.4
Exp/Cntr=0.3,0.1

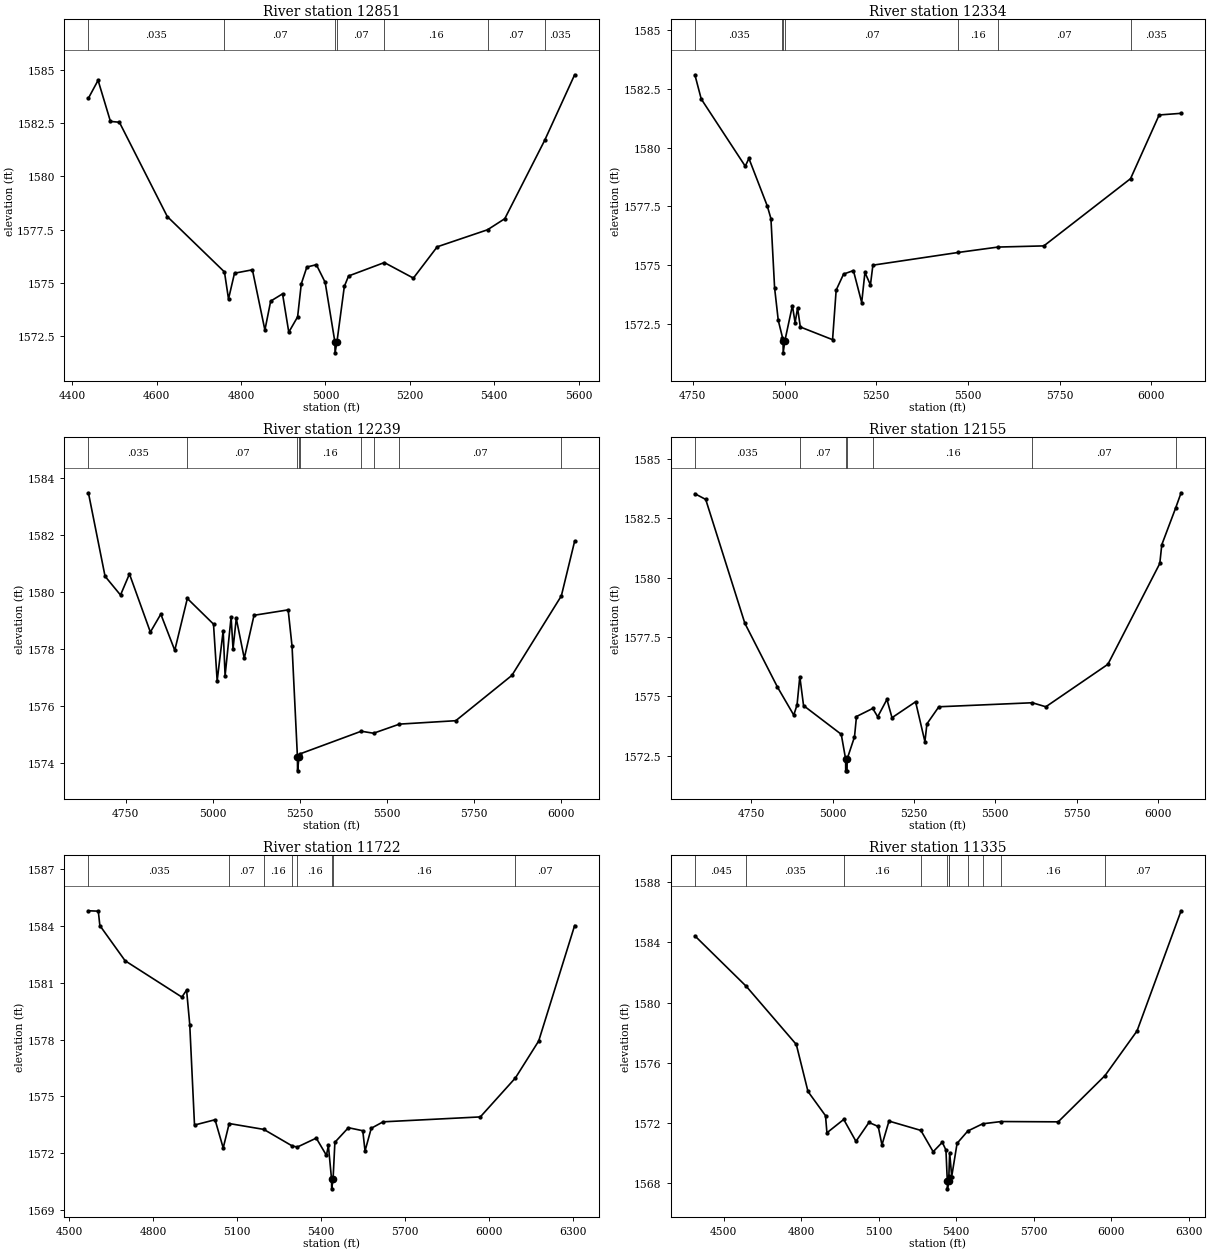
Type RM Length L Ch R = 1,12851,517,517,517
BEGIN DESCRIPTION:
Mapping XS 3c296eac
END DESCRIPTION:
XS GIS Cut Line= 3
      1600406.00      6961770.62      1600732.40      6961308.80
      1600725.46      6960722.46
#Sta/Elev= 30
  4438.6 1583.67  4461.5 1584.51  4490.8 1582.58  4512.0 1582.54  4625.5 1578.11
  4760.9 1575.51  4770.5 1574.24  4784.7 1575.45  4827.1 1575.61  4856.7 1572.78
  4870.4 1574.14  4898.5 1574.48  4913.3 1572.68  4934.2 1573.40  4942.9 1574.95
  4956.1 1575.74  4978.6 1575.85  4999.5 1575.02  5022.6 1572.21  5022.9 1571.71
  5027.3 1572.21  5044.9 1574.83  5054.9 1575.32  5139.7 1575.95  5208.5 1575.22
  5264.9 1576.69  5384.1 1577.49  5425.0 1578.01  5519.5 1581.69  5590.5 1584.77
#Mann=7,-1,0
  4438.6   0.035       0  4760.9    0.07       0  5022.6    0.07       0
  5027.3    0.07       0  5139.7    0.16       0  5384.1    0.07       0
  5519.5   0.035       0
Bank Sta=5022.6,5027.3
Exp/Cntr=0.3,0.1

Type RM Length L Ch R = 1,12334,95,95,95
BEGIN DESCRIPTION:
Mapping XS 71721f1a
END DESCRIPTION:
XS GIS Cut Line= 5
      1600447.71      6961781.20      1600690.73      6961775.99
      1600767.12      6961706.55      1600777.54      6961619.74
      1601600.20      6961276.10
#Sta/Elev= 30
  4755.6 1583.10  4772.9 1582.07  4892.9 1579.21  4902.9 1579.54  4952.9 1577.52
  4962.9 1576.98  4972.9 1574.03  4982.9 1572.65  4994.4 1571.92  4996.0 1571.77
  4996.3 1571.27  5000.7 1571.77  5021.4 1573.28  5028.8 1572.55  5035.5 1573.18
  5043.0 1572.37  5130.9 1571.83  5140.7 1573.94  5160.9 1574.62  5187.7 1574.77
  5210.3 1573.41  5219.1 1574.69  5234.1 1574.16  5240.8 1575.00  5473.1 1575.54
  5581.7 1575.77  5706.8 1575.82  5943.1 1578.68  6021.1 1581.39  6080.9 1581.46
#Mann=7,-1,0
  4755.6   0.035       0  4994.4    0.07       0  4996.0    0.07       0
  5000.7    0.07       0  5473.1    0.16       0  5581.7    0.07       0
  5943.1   0.035       0
Bank Sta=4996,5000.7
Exp/Cntr=0.3,0.1

Type RM Length L Ch R = 1,12239,84,84,84
BEGIN DESCRIPTION:
Mapping XS 43c77259
END DESCRIPTION:
XS GIS Cut Line= 5
      1600397.29      6961828.07      1600751.50      6961847.17
      1600833.10      6961808.98      1600836.57      6961689.19
      1601596.96      6961350.66
#Sta/Elev= 30
  4642.7 1583.47  4690.5 1580.54  4734.9 1579.88  4760.6 1580.62  4820.7 1578.58
  4850.7 1579.21  4890.8 1577.94  4926.9 1579.76  5002.1 1578.86  5012.6 1576.87
  5029.9 1578.63  5035.4 1577.05  5052.7 1579.11  5058.2 1577.99  5067.5 1579.06
  5090.5 1577.66  5118.5 1579.17  5216.6 1579.36  5227.8 1578.08  5243.2 1574.21
  5243.6 1573.71  5247.9 1574.21  5249.5 1574.30  5426.6 1575.10  5461.9 1575.03
  5536.4 1575.35  5698.2 1575.47  5859.4 1577.06  6001.5 1579.85  6039.7 1581.77
#Mann=9,-1,0
  4642.7   0.035       0  4926.9    0.07       0  5243.2    0.07       0
  5247.9    0.07       0  5249.5    0.16       0  5426.6    0.07       0
  5461.9    0.16       0  5536.4    0.07       0  6001.5   0.035       0
Bank Sta=5243.2,5247.9
Exp/Cntr=0.3,0.1

Type RM Length L Ch R = 1,12155,433,433,433
BEGIN DESCRIPTION:
Mapping XS 23e545ce
END DESCRIPTION:
XS GIS Cut Line= 4
      1600301.80      6961888.84      1600721.98      6961920.09
      1600829.62      6961892.31      1601656.00      6961399.26
#Sta/Elev= 30
  4576.6 1583.54  4609.9 1583.30  4730.2 1578.08  4830.5 1575.39  4880.6 1574.21
  4890.7 1574.64  4899.2 1575.83  4910.7 1574.61  5026.6 1573.40  5040.0 1572.36
  5040.3 1571.86  5044.4 1571.86  5044.7 1572.36  5067.3 1573.29  5073.4 1574.15
  5123.3 1574.49  5138.7 1574.14  5167.0 1574.87  5182.6 1574.10  5255.1 1574.77
  5283.8 1573.09  5290.0 1573.84  5326.6 1574.56  5614.0 1574.73  5655.5 1574.56
  5846.3 1576.35  6005.9 1580.60  6012.0 1581.39  6054.4 1582.93  6071.4 1583.58
#Mann=7,-1,0
  4576.6   0.035       0  4899.2    0.07       0  5040.0    0.07       0
  5044.7    0.07       0  5123.3    0.16       0  5614.0    0.07       0
  6054.4   0.035       0
Bank Sta=5040,5044.7
Exp/Cntr=0.3,0.1

Type RM Length L Ch R = 1,11722,387,387,387
BEGIN DESCRIPTION:
Mapping XS 1c62ac75
END DESCRIPTION:
XS GIS Cut Line= 3
      1600269.51      6962519.07      1600654.97      6962331.55
      1601753.91      6961620.62
#Sta/Elev= 30
  4569.3 1584.81  4604.6 1584.79  4610.2 1584.03  4700.4 1582.17  4903.3 1580.25
  4920.1 1580.62  4931.4 1578.80  4948.4 1573.49  5021.8 1573.77  5051.0 1572.28
  5072.3 1573.57  5196.1 1573.26  5298.2 1572.38  5316.2 1572.33  5383.5 1572.80
  5419.8 1571.89  5426.8 1572.41  5438.2 1570.62  5438.6 1570.12  5443.5 1570.62
  5450.1 1572.58  5498.3 1573.35  5549.7 1573.19  5557.8 1572.12  5580.0 1573.32
  5622.3 1573.66  5969.8 1573.92  6095.2 1575.98  6178.3 1577.93  6306.8 1584.03
#Mann=8,-1,0
  4569.3   0.035       0  5072.3    0.07       0  5196.1    0.16       0
  5298.2    0.07       0  5316.2    0.16       0  5438.2   0.035       0
  5443.5    0.16       0  6095.2    0.07       0
Bank Sta=5438.2,5443.5
Exp/Cntr=0.3,0.1

Type RM Length L Ch R = 1,11335,329,329,329
BEGIN DESCRIPTION:
Mapping XS 3d34e319
END DESCRIPTION:
XS GIS Cut Line= 3
      1600376.31      6962823.74      1600925.80      6962558.11
      1601911.41      6961754.54
#Sta/Elev= 30
  4389.1 1584.44  4588.6 1581.07  4781.7 1577.21  4826.9 1574.08  4894.7 1572.47
  4900.2 1571.33  4965.2 1572.22  5012.6 1570.76  5062.9 1572.02  5098.8 1571.75
  5113.2 1570.52  5140.4 1572.11  5263.7 1571.49  5311.4 1570.07  5346.8 1570.70
  5360.9 1570.18  5366.2 1568.10  5366.6 1567.60  5371.5 1568.10  5372.2 1568.45
  5375.3 1570.01  5383.2 1568.42  5404.0 1570.63  5445.5 1571.45  5503.0 1571.93
  5574.8 1572.08  5795.3 1572.06  5976.6 1575.14  6100.5 1578.11  6271.1 1586.11
#Mann=11,-1,0
  4389.1   0.045       0  4588.6   0.035       0  4965.2    0.16       0
  5263.7   0.035       0  5366.2    0.07       0  5371.5   0.035       0
  5372.2    0.07       0  5445.5   0.035       0  5503.0    0.07       0
  5574.8    0.16       0  5976.6    0.07       0
Bank Sta=5366.2,5371.5
Exp/Cntr=0.3,0.1

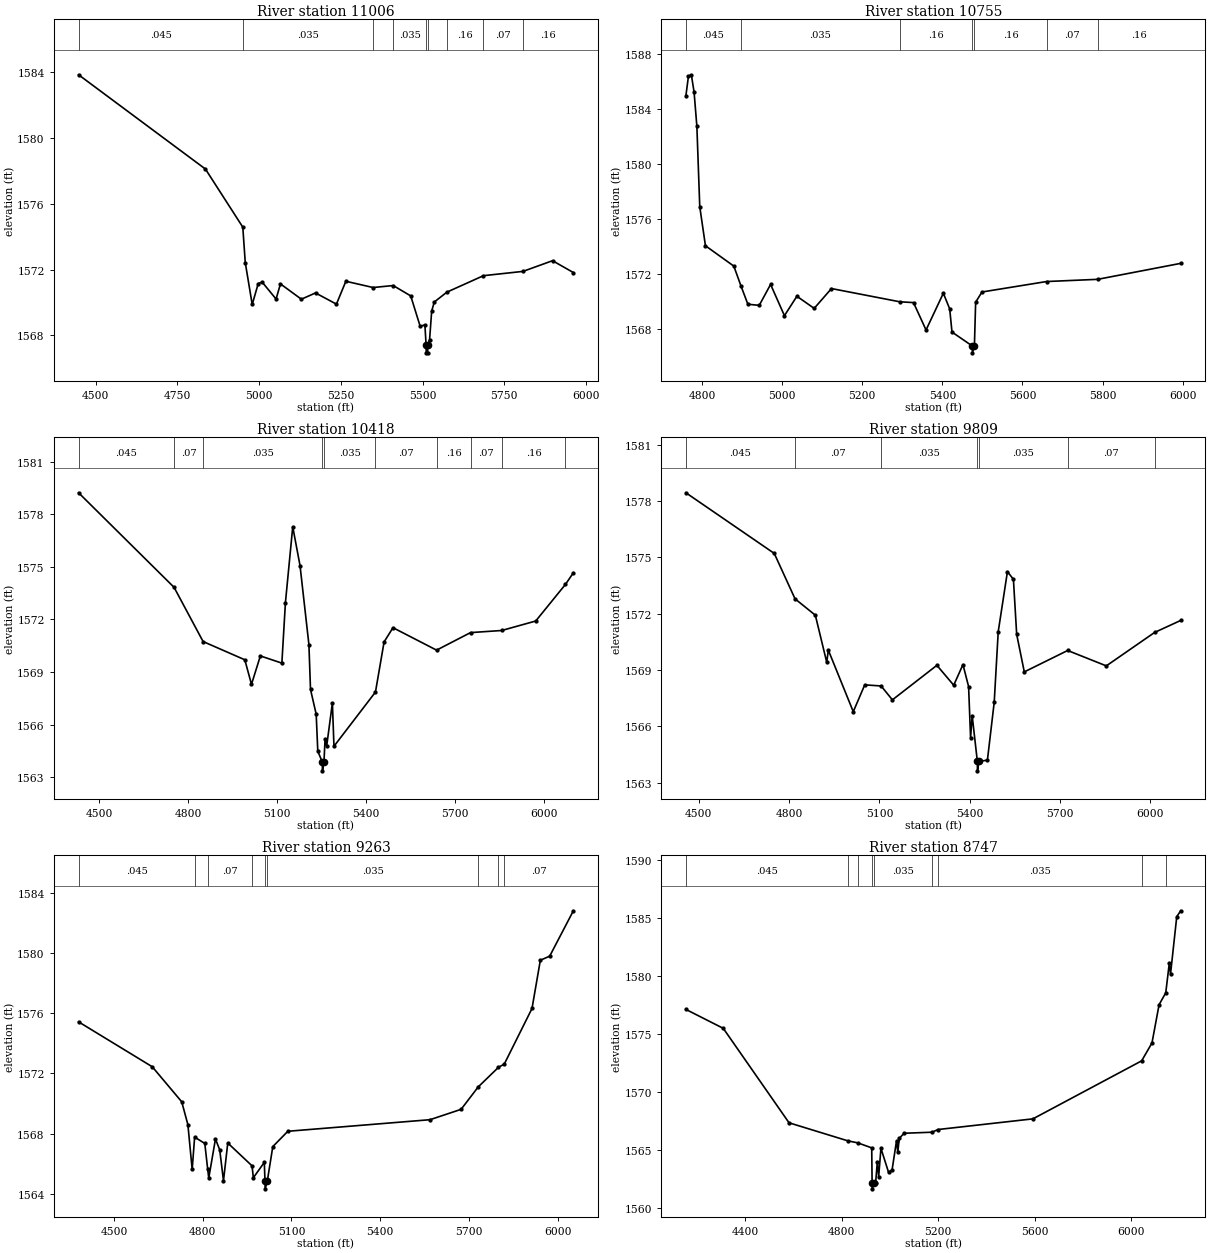
Type RM Length L Ch R = 1,11006,251,251,251
BEGIN DESCRIPTION:
Mapping XS 968f6183
END DESCRIPTION:
XS GIS Cut Line= 3
      1600483.10      6963138.84      1600951.85      6962849.78
      1601553.13      6962097.45
#Sta/Elev= 30
  4447.5 1583.84  4835.6 1578.11  4949.9 1574.58  4957.4 1572.43  4978.7 1569.88
  4997.1 1571.15  5009.1 1571.24  5051.7 1570.21  5065.1 1571.13  5129.1 1570.20
  5172.4 1570.58  5236.4 1569.90  5265.2 1571.29  5348.6 1570.91  5410.1 1571.03
  5463.7 1570.40  5492.6 1568.55  5507.0 1568.64  5510.7 1567.44  5511.1 1566.94
  5515.6 1566.94  5516.0 1567.44  5521.4 1567.74  5527.8 1569.48  5535.8 1570.03
  5574.4 1570.63  5686.3 1571.63  5807.0 1571.89  5897.6 1572.54  5961.3 1571.82
#Mann=9,-1,0
  4447.5   0.045       0  4949.9   0.035       0  5348.6    0.16       0
  5410.1   0.035       0  5510.7   0.035       0  5516.0   0.035       0
  5574.4    0.16       0  5686.3    0.07       0  5807.0    0.16       0
Bank Sta=5510.7,5516
Exp/Cntr=0.3,0.1

Type RM Length L Ch R = 1,10755,337,337,337
BEGIN DESCRIPTION:
Mapping XS ae297f55
END DESCRIPTION:
XS GIS Cut Line= 3
      1600964.86      6963086.76      1601139.35      6962925.30
      1601633.88      6962058.36
#Sta/Elev= 30
  4759.4 1584.98  4765.7 1586.38  4773.0 1586.50  4779.8 1585.25  4786.8 1582.75
  4794.0 1576.92  4808.2 1574.08  4879.1 1572.60  4897.2 1571.14  4914.2 1569.83
  4942.6 1569.75  4970.9 1571.27  5005.5 1569.00  5036.6 1570.41  5079.8 1569.53
  5123.0 1570.97  5293.3 1570.01  5327.9 1569.95  5359.2 1567.96  5402.4 1570.63
  5418.3 1569.49  5424.0 1567.81  5474.6 1566.80  5475.1 1566.30  5480.0 1566.80
  5483.1 1569.98  5498.9 1570.72  5660.2 1571.48  5787.8 1571.64  5995.2 1572.80
#Mann=7,-1,0
  4759.4   0.045       0  4897.2   0.035       0  5293.3    0.16       0
  5474.6   0.035       0  5480.0    0.16       0  5660.2    0.07       0
  5787.8    0.16       0
Bank Sta=5474.6,5480
Exp/Cntr=0.3,0.1

Type RM Length L Ch R = 1,10418,609,609,609
BEGIN DESCRIPTION:
Mapping XS 501ab682
END DESCRIPTION:
XS GIS Cut Line= 3
      1600894.56      6963412.27      1601355.49      6963076.34
      1601750.53      6962049.35
#Sta/Elev= 30
  4429.6 1579.22  4752.0 1573.83  4850.0 1570.74  4990.9 1569.70  5013.4 1568.30
  5043.4 1569.92  5116.0 1569.51  5128.0 1572.96  5152.7 1577.28  5177.3 1575.07
  5207.3 1570.57  5212.7 1568.01  5231.9 1566.60  5237.3 1564.49  5252.6 1563.87
  5253.0 1563.37  5258.1 1563.87  5261.9 1565.17  5267.3 1564.78  5286.6 1567.24
  5291.9 1564.77  5432.0 1567.86  5461.2 1570.72  5491.2 1571.53  5638.4 1570.25
  5753.1 1571.25  5858.4 1571.37  5973.2 1571.91  6073.7 1574.00  6100.3 1574.66
#Mann=10,-1,0
  4429.6   0.045       0  4752.0    0.07       0  4850.0   0.035       0
  5252.6   0.035       0  5258.1   0.035       0  5432.0    0.07       0
  5638.4    0.16       0  5753.1    0.07       0  5858.4    0.16       0
  6073.7    0.07       0
Bank Sta=5252.6,5258.1
Exp/Cntr=0.3,0.1

Type RM Length L Ch R = 1,9809,546,546,546
BEGIN DESCRIPTION:
Mapping XS 31e89aa1
END DESCRIPTION:
XS GIS Cut Line= 3
      1601248.47      6963857.82      1601412.52      6963339.62
      1601787.52      6962305.78
#Sta/Elev= 30
  4457.3 1578.44  4750.8 1575.21  4819.8 1572.79  4887.2 1571.92  4925.1 1569.41
  4930.3 1570.06  5013.2 1566.78  5051.3 1568.21  5105.7 1568.15  5143.1 1567.41
  5290.9 1569.25  5346.8 1568.19  5377.5 1569.29  5396.2 1568.12  5402.8 1565.39
  5408.1 1566.57  5425.3 1564.13  5425.7 1563.63  5430.8 1564.13  5458.7 1564.20
  5481.3 1567.28  5494.6 1571.04  5525.2 1574.24  5545.1 1573.83  5555.9 1570.90
  5581.2 1568.90  5725.3 1570.04  5853.6 1569.22  6013.9 1571.00  6100.6 1571.64
#Mann=7,-1,0
  4457.3   0.045       0  4819.8    0.07       0  5105.7   0.035       0
  5425.3    0.07       0  5430.8   0.035       0  5725.3    0.07       0
  6013.9   0.035       0
Bank Sta=5425.3,5430.8
Exp/Cntr=0.3,0.1

Type RM Length L Ch R = 1,9263,516,516,516
BEGIN DESCRIPTION:
Mapping XS 2c91f0e7
END DESCRIPTION:
XS GIS Cut Line= 3
      1601454.16      6963805.80      1601834.40      6963313.58
      1602290.06      6962365.80
#Sta/Elev= 30
  4380.0 1575.43  4629.3 1572.44  4728.9 1570.11  4749.7 1568.59  4764.2 1565.61
  4772.5 1567.76  4806.9 1567.34  4816.7 1565.62  4820.3 1565.04  4843.0 1567.64
  4857.4 1566.91  4870.1 1564.86  4884.6 1567.37  4966.7 1565.85  4971.1 1565.06
  5008.2 1566.08  5010.5 1564.82  5011.0 1564.32  5018.2 1564.82  5036.9 1567.13
  5087.8 1568.15  5568.7 1568.92  5673.9 1569.61  5731.7 1571.10  5800.0 1572.40
  5819.9 1572.62  5913.7 1576.32  5941.9 1579.53  5973.5 1579.80  6053.6 1582.82
#Mann=9,-1,0
  4380.0   0.045       0  4772.5   0.035       0  4816.7    0.07       0
  4966.7   0.035       0  5010.5   0.035       0  5018.2   0.035       0
  5731.7    0.07       0  5800.0   0.035       0  5819.9    0.07       0
Bank Sta=5010.5,5018.2
Exp/Cntr=0.3,0.1

Type RM Length L Ch R = 1,8747,458,458,458
BEGIN DESCRIPTION:
Mapping XS 008de528
END DESCRIPTION:
XS GIS Cut Line= 3
      1601355.21      6963954.21      1602133.88      6963610.45
      1602409.69      6962442.14
#Sta/Elev= 30
  4153.7 1577.15  4308.6 1575.52  4581.4 1567.38  4824.6 1565.83  4866.6 1565.65
  4924.2 1565.22  4925.8 1562.19  4926.3 1561.69  4933.5 1562.19  4940.5 1562.23
  4947.5 1564.04  4953.0 1562.73  4962.4 1565.18  4994.1 1563.11  5008.7 1563.33
  5027.2 1565.85  5032.3 1564.83  5038.2 1566.04  5058.8 1566.48  5175.0 1566.57
  5198.7 1566.80  5592.6 1567.72  6043.5 1572.72  6086.3 1574.26  6115.8 1577.56
  6143.4 1578.58  6158.1 1581.13  6163.2 1580.20  6189.0 1585.14  6205.3 1585.65
#Mann=9,-1,0
  4153.7   0.045       0  4824.6    0.07       0  4866.6   0.035       0
  4925.8   0.035       0  4933.5   0.035       0  5175.0    0.07       0
  5198.7   0.035       0  6043.5    0.07       0  6143.4   0.035       0
Bank Sta=4925.8,4933.5
Exp/Cntr=0.3,0.1

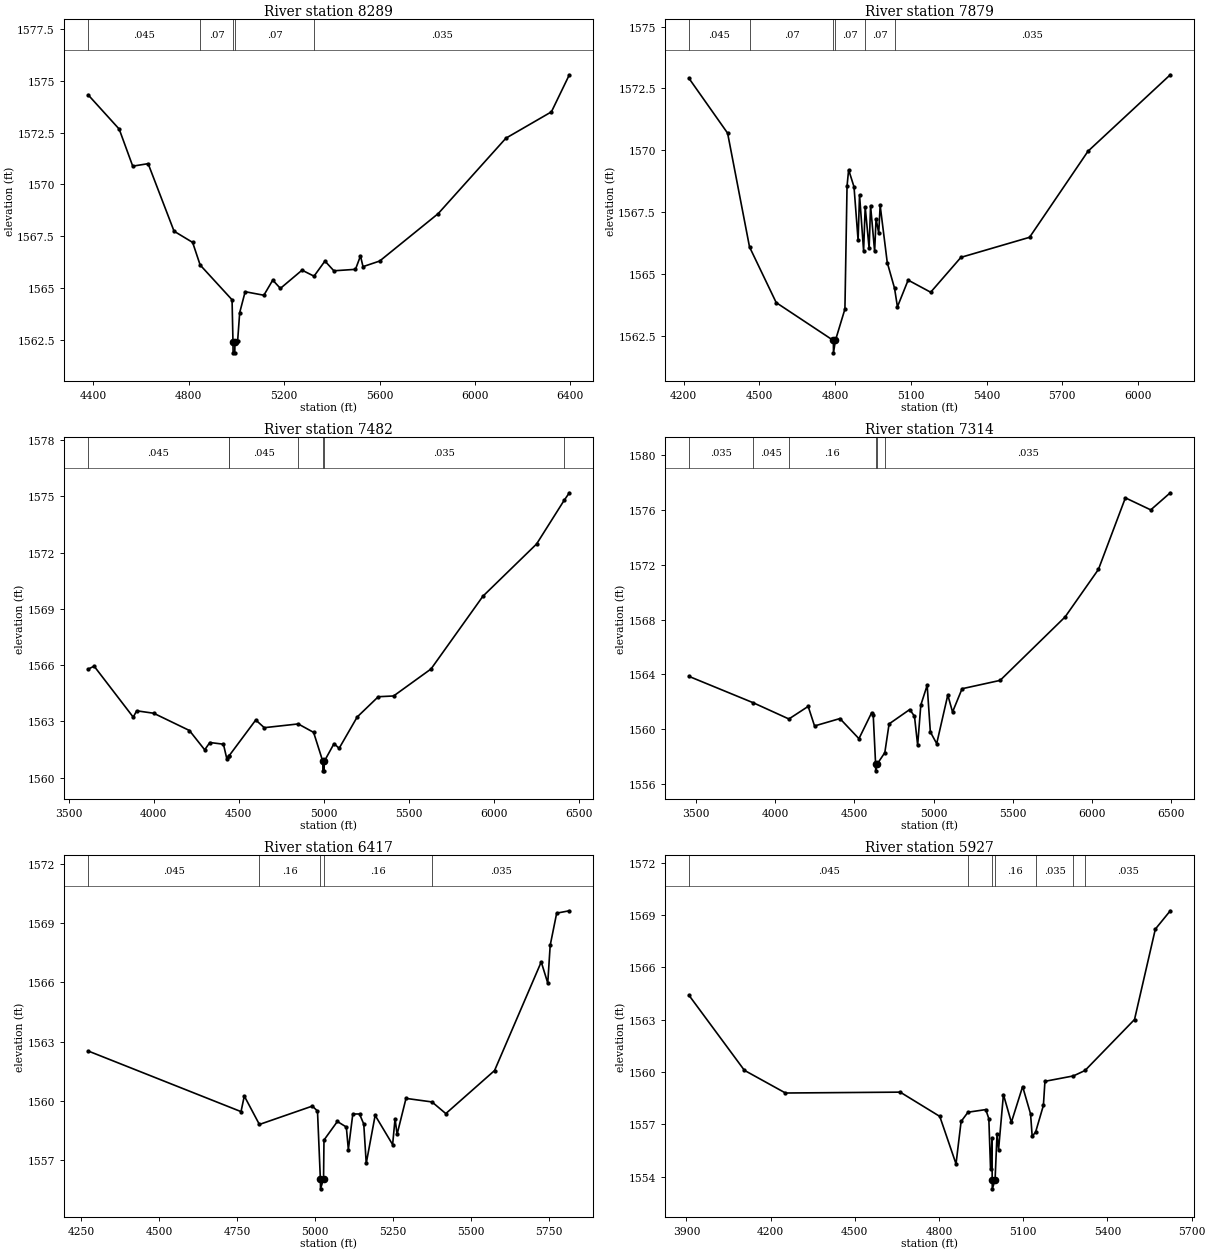
Type RM Length L Ch R = 1,8289,410,410,410
BEGIN DESCRIPTION:
Mapping XS 9450b33d
END DESCRIPTION:
XS GIS Cut Line= 3
      1601903.08      6964455.30      1602254.65      6963943.14
      1602684.33      6962615.03
#Sta/Elev= 30
  4378.6 1574.32  4508.6 1572.67  4565.4 1570.88  4630.0 1571.00  4738.7 1567.74
  4816.5 1567.20  4848.0 1566.11  4981.8 1564.43  4985.7 1562.37  4986.2 1561.87
  4993.3 1561.87  4993.8 1562.37  5005.2 1562.45  5013.8 1563.81  5036.7 1564.82
  5115.1 1564.65  5152.4 1565.38  5184.4 1564.98  5275.2 1565.86  5325.4 1565.57
  5371.2 1566.30  5408.5 1565.83  5499.2 1565.90  5520.2 1566.55  5530.7 1566.03
  5600.5 1566.30  5846.0 1568.59  6129.8 1572.23  6320.5 1573.50  6395.7 1575.29
#Mann=5,-1,0
  4378.6   0.045       0  4848.0    0.07       0  4985.7    0.07       0
  4993.8    0.07       0  5325.4   0.035       0
Bank Sta=4985.7,4993.8
Exp/Cntr=0.3,0.1

Type RM Length L Ch R = 1,7879,397,397,397
BEGIN DESCRIPTION:
Mapping XS 73ece6ba
END DESCRIPTION:
XS GIS Cut Line= 4
      1602169.07      6964534.61      1602544.06      6964017.27
      1602610.03      6963895.74      1602738.50      6962774.21
#Sta/Elev= 30
  4221.8 1572.90  4374.4 1570.69  4461.2 1566.09  4566.9 1563.84  4793.3 1562.31
  4793.8 1561.81  4801.4 1562.31  4839.1 1563.58  4847.5 1568.55  4853.8 1569.21
  4875.1 1568.52  4891.3 1566.36  4897.0 1568.20  4913.1 1565.93  4919.4 1567.71
  4935.0 1566.03  4940.7 1567.76  4956.8 1565.91  4962.5 1567.23  4973.0 1566.65
  4978.7 1567.77  5006.8 1565.46  5035.7 1564.42  5047.1 1563.67  5089.5 1564.75
  5178.8 1564.26  5298.7 1565.67  5570.5 1566.48  5802.0 1569.96  6127.9 1573.05
#Mann=6,-1,0
  4221.8   0.045       0  4461.2    0.07       0  4793.3    0.07       0
  4801.4    0.07       0  4919.4    0.07       0  5035.7   0.035       0
Bank Sta=4793.3,4801.4
Exp/Cntr=0.3,0.1

Type RM Length L Ch R = 1,7482,168,168,168
BEGIN DESCRIPTION:
Mapping XS f16bd459
END DESCRIPTION:
XS GIS Cut Line= 3
      1602868.92      6965472.99      1602875.31      6964086.37
      1602836.24      6962645.43
#Sta/Elev= 30
  3614.8 1565.79  3649.8 1565.95  3879.8 1563.23  3899.8 1563.57  3999.8 1563.44
  4209.8 1562.52  4299.8 1561.49  4329.8 1561.88  4409.8 1561.79  4429.8 1561.01
  4440.8 1561.14  4443.0 1561.17  4599.8 1563.08  4649.8 1562.67  4849.4 1562.87
  4939.8 1562.42  4994.0 1560.87  4994.5 1560.37  5001.7 1560.37  5002.2 1560.87
  5059.8 1561.82  5089.8 1561.57  5196.0 1563.24  5319.9 1564.32  5410.0 1564.36
  5630.0 1565.80  5935.2 1569.68  6250.3 1572.46  6411.8 1574.78  6442.9 1575.19
#Mann=7,-1,0
  3614.8   0.045       0  4440.8   0.035       0  4443.0   0.045       0
  4849.4   0.035       0  4994.0   0.035       0  5002.2   0.035       0
  6411.8    0.07       0
Bank Sta=4994,5002.2
Exp/Cntr=0.3,0.1

Type RM Length L Ch R = 1,7314,897,897,897
BEGIN DESCRIPTION:
Mapping XS ea7221f5
END DESCRIPTION:
XS GIS Cut Line= 5
      1603077.25      6965678.75      1603027.21      6964142.79
      1603022.87      6962667.09      1603022.87      6962662.75
      1603018.54      6962645.40
#Sta/Elev= 30
  3458.0 1563.85  3863.6 1561.92  4087.5 1560.74  4209.1 1561.66  4249.2 1560.23
  4409.3 1560.77  4529.3 1559.30  4609.4 1561.20  4619.4 1561.02  4634.3 1557.45
  4634.8 1556.95  4644.4 1557.45  4692.4 1558.28  4719.4 1560.38  4849.5 1561.43
  4879.5 1560.94  4899.5 1558.82  4919.5 1561.76  4959.5 1563.20  4979.6 1559.79
  5019.6 1558.94  5089.6 1562.49  5119.6 1561.25  5179.6 1562.95  5419.6 1563.56
  5829.6 1568.20  6039.6 1571.67  6209.6 1576.90  6369.6 1576.02  6492.7 1577.27
#Mann=6,-1,0
  3458.0   0.035       0  3863.6   0.045       0  4087.5    0.16       0
  4634.3   0.035       0  4644.4    0.16       0  4692.4   0.035       0
Bank Sta=4634.3,4644.4
Exp/Cntr=0.3,0.1

Type RM Length L Ch R = 1,6417,490,490,490
BEGIN DESCRIPTION:
Mapping XS 9ff3582d
END DESCRIPTION:
XS GIS Cut Line= 3
      1603116.44      6965460.53      1603394.23      6964790.36
      1604021.38      6964267.16
#Sta/Elev= 30
  4273.3 1562.53  4763.2 1559.46  4773.7 1560.25  4822.1 1558.81  4991.8 1559.74
  5008.3 1559.49  5017.5 1556.05  5018.0 1555.55  5027.7 1556.05  5029.1 1558.02
  5072.0 1558.96  5100.7 1558.68  5107.2 1557.54  5121.5 1559.34  5143.0 1559.34
  5156.6 1558.83  5164.5 1556.84  5193.1 1559.27  5249.1 1557.79  5256.9 1559.10
  5263.4 1558.31  5292.0 1560.13  5375.3 1559.95  5419.6 1559.36  5575.8 1561.54
  5725.4 1567.04  5746.3 1565.97  5754.1 1567.88  5774.9 1569.51  5815.5 1569.63
#Mann=5,-1,0
  4273.3   0.045       0  4822.1    0.16       0  5017.5    0.07       0
  5027.7    0.16       0  5375.3   0.035       0
Bank Sta=5017.5,5027.7
Exp/Cntr=0.3,0.1

Type RM Length L Ch R = 1,5927,522,522,522
BEGIN DESCRIPTION:
Mapping XS 6ab9fe7b
END DESCRIPTION:
XS GIS Cut Line= 3
      1603383.80      6965988.30      1603814.37      6964991.75
      1604081.57      6964422.65
#Sta/Elev= 30
  3909.5 1564.39  4106.5 1560.10  4252.9 1558.80  4661.6 1558.85  4802.6 1557.46
  4860.5 1554.74  4878.6 1557.17  4903.2 1557.70  4966.5 1557.85  4977.4 1557.33
  4983.5 1554.44  4988.9 1556.24  4989.3 1553.81  4989.8 1553.31  4999.6 1553.81
  5006.6 1556.45  5012.1 1555.56  5029.4 1558.71  5057.7 1557.12  5097.8 1559.17
  5126.1 1557.60  5131.8 1556.32  5144.0 1556.56  5171.8 1558.09  5177.3 1559.47
  5278.9 1559.78  5320.1 1560.09  5496.4 1563.01  5570.6 1568.19  5623.8 1569.24
#Mann=7,-1,0
  3909.5   0.045       0  4903.2    0.16       0  4989.3    0.07       0
  4999.6    0.16       0  5144.0   0.035       0  5278.9    0.16       0
  5320.1   0.035       0
Bank Sta=4989.3,4999.6
Exp/Cntr=0.3,0.1