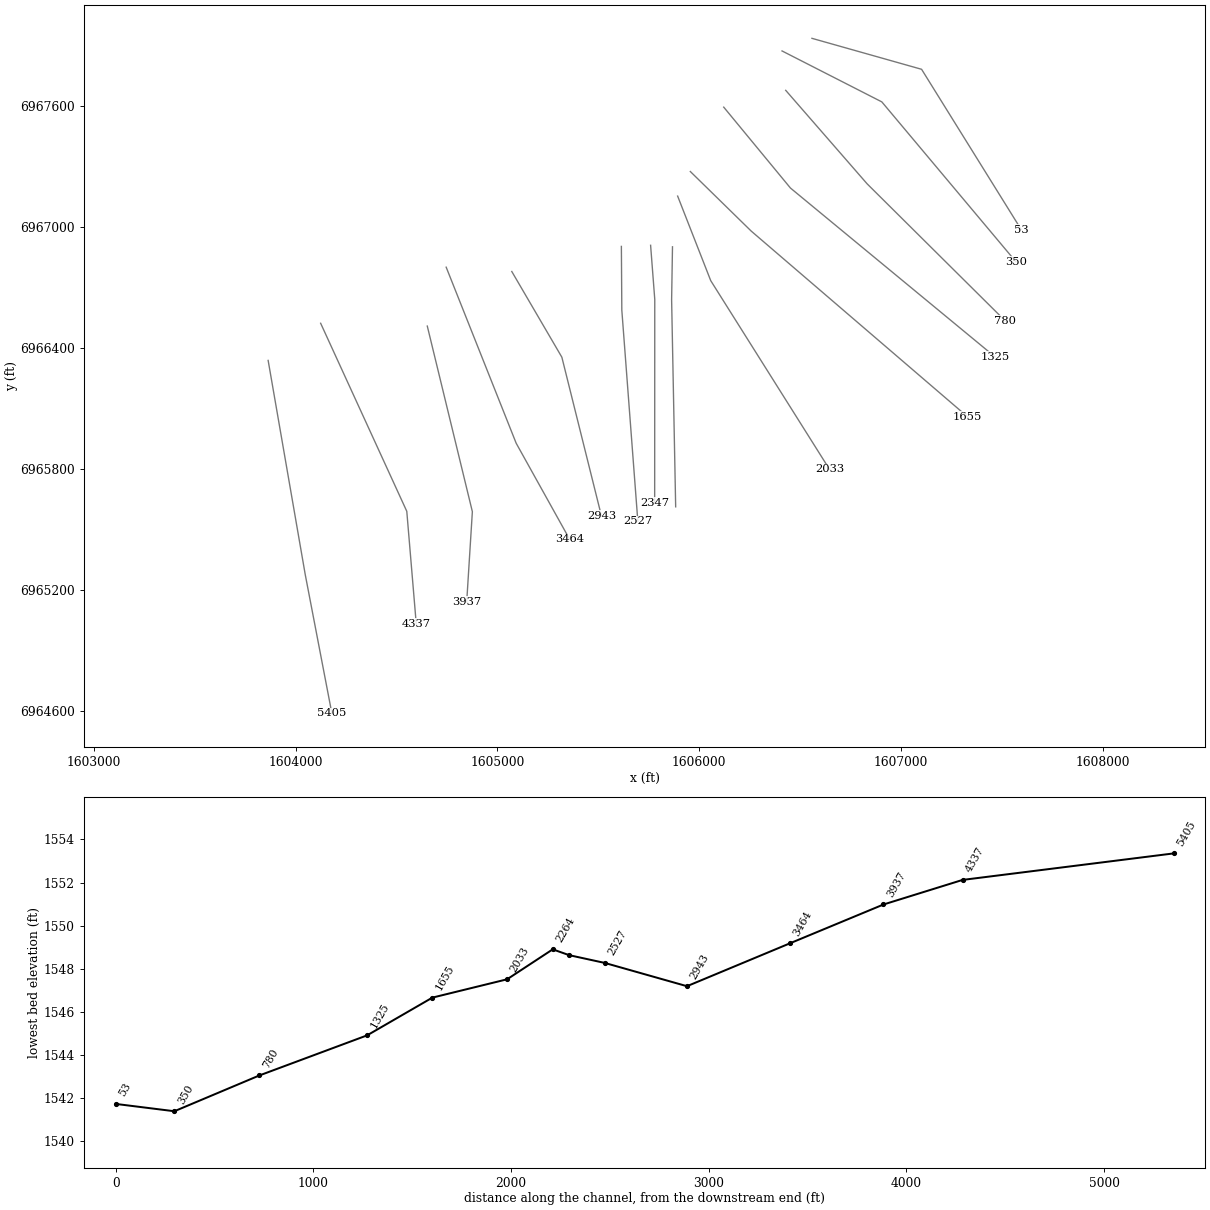
HEC-RAS study Chimney Creek 1118.prj: Chimney Creek 1118 Base Level Engineering

--- Chimney Creek 1118.g01 (geometry) --- (continued)

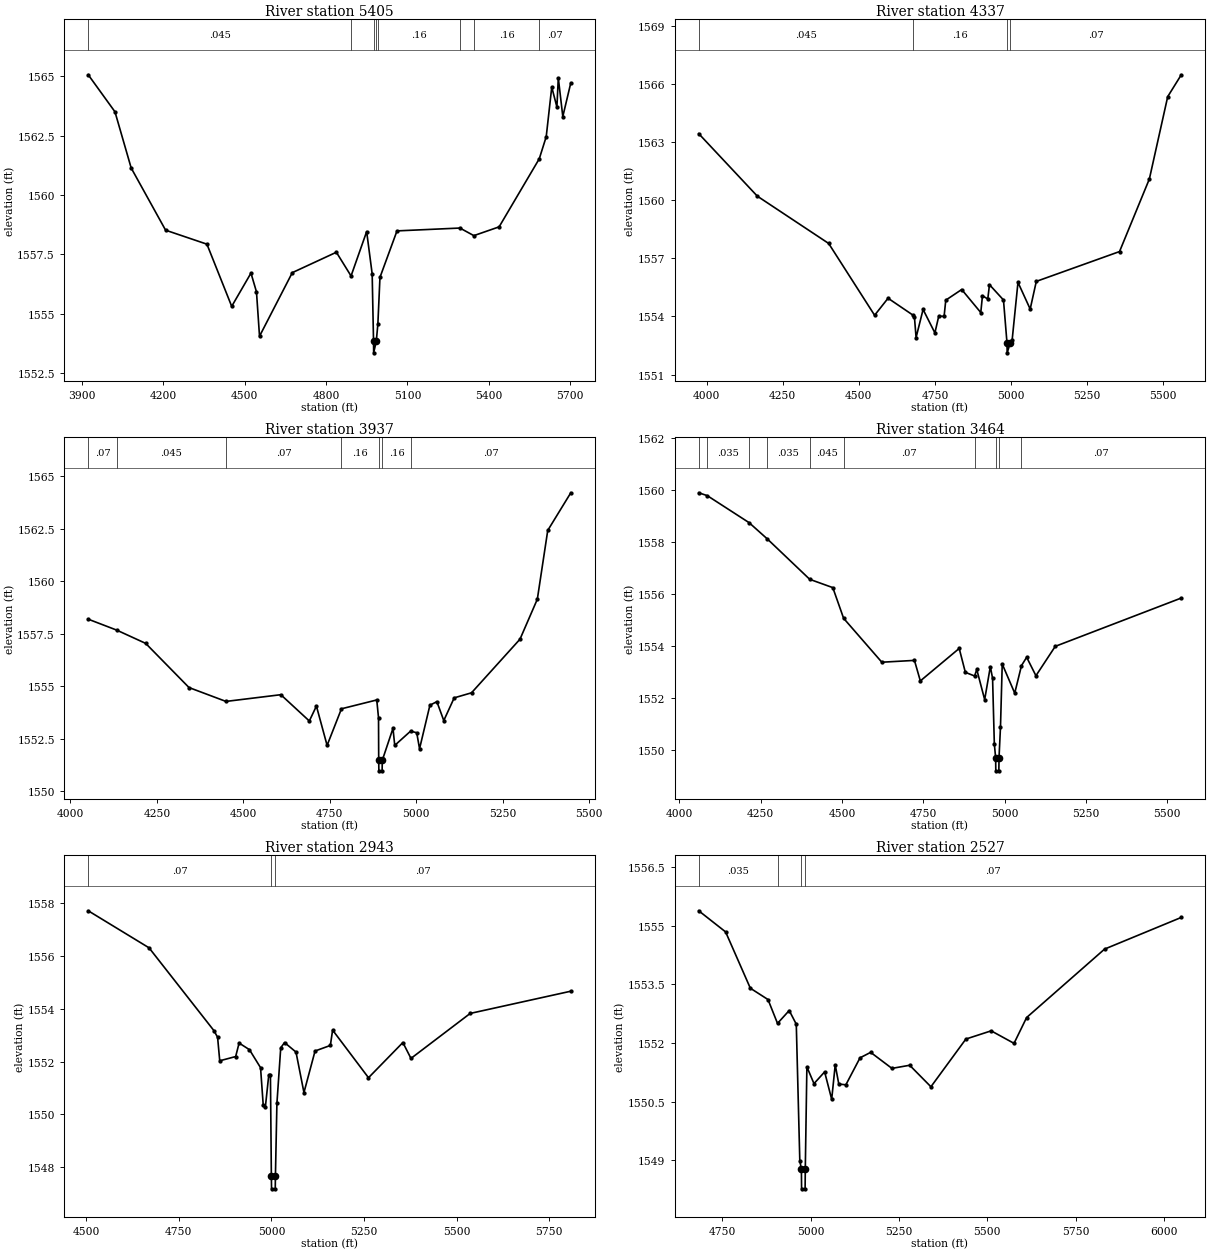
Type RM Length L Ch R = 1,5405,1068,1068,1068
BEGIN DESCRIPTION:
Mapping XS 87a4afb0
END DESCRIPTION:
XS GIS Cut Line= 3
      1603862.98      6966338.94      1604047.01      6965276.47
      1604178.94      6964589.01
#Sta/Elev= 30
  3923.6 1565.07  4022.1 1563.51  4081.9 1561.14  4208.7 1558.52  4361.0 1557.93
  4452.3 1555.31  4523.3 1556.71  4543.6 1555.92  4554.8 1554.05  4675.6 1556.73
  4838.0 1557.59  4892.1 1556.59  4949.6 1558.46  4969.9 1556.68  4974.9 1553.85
  4975.4 1553.35  4985.2 1553.85  4990.9 1554.56  4998.6 1556.53  5061.4 1558.49
  5293.3 1558.61  5344.6 1558.29  5437.7 1558.66  5585.7 1561.53  5611.3 1562.46
  5631.7 1564.55  5650.7 1563.71  5655.8 1564.94  5672.4 1563.31  5701.9 1564.73
#Mann=8,-1,0
  3923.6   0.045       0  4892.1    0.07       0  4974.9    0.07       0
  4985.2    0.07       0  4990.9    0.16       0  5293.3    0.07       0
  5344.6    0.16       0  5585.7    0.07       0
Bank Sta=4974.9,4985.2
Exp/Cntr=0.3,0.1

Type RM Length L Ch R = 1,4337,400,400,400
BEGIN DESCRIPTION:
Mapping XS eb97342c
END DESCRIPTION:
XS GIS Cut Line= 3
      1604123.27      6966523.11      1604550.34      6965590.84
      1604597.22      6965033.55
#Sta/Elev= 30
  3974.3 1563.44  4166.9 1560.21  4401.0 1557.77  4551.9 1554.06  4596.1 1554.94
  4676.7 1554.08  4682.6 1553.99  4688.1 1552.91  4711.1 1554.36  4749.9 1553.15
  4762.6 1554.02  4780.1 1554.00  4785.6 1554.84  4837.9 1555.39  4900.6 1554.20
  4906.1 1555.07  4923.6 1554.90  4929.1 1555.64  4975.1 1554.85  4986.7 1552.62
  4987.2 1552.12  4997.1 1552.62  5003.7 1552.80  5022.7 1555.76  5062.8 1554.38
  5082.9 1555.81  5356.2 1557.35  5454.2 1561.10  5514.4 1565.35  5559.0 1566.48
#Mann=4,-1,0
  3974.3   0.045       0  4676.7    0.16       0  4986.7    0.07       0
  4997.1    0.07       0
Bank Sta=4986.7,4997.1
Exp/Cntr=0.3,0.1

Type RM Length L Ch R = 1,3937,473,473,473
BEGIN DESCRIPTION:
Mapping XS 53b6a1a8
END DESCRIPTION:
XS GIS Cut Line= 3
      1604651.96      6966509.19      1604875.48      6965589.08
      1604847.37      6965141.43
#Sta/Elev= 30
  4051.4 1558.19  4133.8 1557.67  4217.5 1557.04  4342.8 1554.94  4449.7 1554.28
  4608.3 1554.60  4690.7 1553.35  4711.2 1554.06  4742.1 1552.19  4783.6 1553.93
  4885.7 1554.35  4890.8 1553.50  4891.3 1551.48  4891.8 1550.98  4901.2 1550.98
  4901.7 1551.48  4932.6 1553.00  4937.7 1552.19  4983.7 1552.87  5001.3 1552.79
  5009.4 1552.03  5039.4 1554.10  5059.5 1554.27  5079.5 1553.37  5109.6 1554.45
  5159.7 1554.69  5299.9 1557.24  5350.0 1559.14  5380.1 1562.41  5446.8 1564.20
#Mann=7,-1,0
  4051.4    0.07       0  4133.8   0.045       0  4449.7    0.07       0
  4783.6    0.16       0  4891.3    0.07       0  4901.7    0.16       0
  4983.7    0.07       0
Bank Sta=4891.3,4901.7
Exp/Cntr=0.3,0.1

Type RM Length L Ch R = 1,3464,521,521,521
BEGIN DESCRIPTION:
Mapping XS 2c311119
END DESCRIPTION:
XS GIS Cut Line= 3
      1604745.65      6966801.15      1605092.67      6965928.35
      1605357.39      6965452.60
#Sta/Elev= 30
  4059.4 1559.88  4085.7 1559.77  4214.3 1558.73  4269.8 1558.11  4400.7 1556.55
  4471.7 1556.23  4504.9 1555.05  4622.4 1553.36  4722.7 1553.43  4740.8 1552.64
  4860.3 1553.89  4879.2 1552.97  4907.6 1552.83  4914.3 1553.08  4938.6 1551.92
  4956.0 1553.19  4962.9 1552.74  4968.3 1550.22  4972.3 1549.68  4972.8 1549.18
  4982.2 1549.18  4982.7 1549.68  4987.2 1550.86  4992.6 1553.29  5031.0 1552.17
  5051.8 1553.23  5067.7 1553.55  5096.2 1552.84  5155.6 1553.97  5543.1 1555.83
#Mann=10,-1,0
  4059.4   0.045       0  4085.7   0.035       0  4214.3   0.045       0
  4269.8   0.035       0  4400.7   0.045       0  4504.9    0.07       0
  4907.6    0.16       0  4972.3    0.07       0  4982.7    0.16       0
  5051.8    0.07       0
Bank Sta=4972.3,4982.7
Exp/Cntr=0.3,0.1

Type RM Length L Ch R = 1,2943,416,416,416
BEGIN DESCRIPTION:
Mapping XS f90e1e38
END DESCRIPTION:
XS GIS Cut Line= 3
      1605070.93      6966779.77      1605319.13      6966354.94
      1605515.38      6965567.96
#Sta/Elev= 30
  4505.4 1557.70  4669.6 1556.30  4844.8 1553.17  4854.7 1552.92  4860.5 1552.03
  4903.5 1552.19  4912.8 1552.70  4940.7 1552.45  4970.7 1551.77  4977.9 1550.36
  4983.7 1550.28  4992.8 1551.48  4997.4 1551.48  4999.9 1547.69  5000.4 1547.19
  5010.4 1547.19  5010.9 1547.69  5014.9 1550.42  5025.2 1552.52  5035.5 1552.72
  5066.4 1552.36  5087.9 1550.83  5117.9 1552.40  5159.2 1552.61  5165.3 1553.19
  5262.2 1551.39  5355.0 1552.72  5376.9 1552.12  5536.8 1553.82  5808.5 1554.66
#Mann=3,-1,0
  4505.4    0.07       0  4999.9    0.07       0  5010.9    0.07       0
Bank Sta=4999.9,5010.9
Exp/Cntr=0.3,0.1

Type RM Length L Ch R = 1,2527,180,180,180
BEGIN DESCRIPTION:
Mapping XS 5b043de2
END DESCRIPTION:
XS GIS Cut Line= 3
      1605614.27      6966904.14      1605616.44      6966588.39
      1605695.84      6965541.55
#Sta/Elev= 30
  4683.5 1555.38  4759.6 1554.84  4829.6 1553.40  4879.6 1553.11  4906.5 1552.50
  4939.6 1552.83  4959.6 1552.48  4969.6 1548.99  4974.1 1548.77  4974.6 1548.27
  4984.6 1548.27  4985.1 1548.77  4989.6 1551.39  5009.7 1550.96  5039.8 1551.26
  5059.8 1550.56  5069.8 1551.44  5079.9 1550.95  5099.9 1550.93  5140.0 1551.62
  5170.1 1551.76  5230.3 1551.35  5280.5 1551.43  5340.6 1550.88  5439.5 1552.10
  5511.1 1552.31  5575.8 1551.99  5611.4 1552.65  5832.0 1554.40  6049.1 1555.21
#Mann=4,-1,0
  4683.5   0.035       0  4906.5    0.07       0  4974.1    0.07       0
  4985.1    0.07       0
Bank Sta=4974.1,4985.1
Exp/Cntr=0.3,0.1

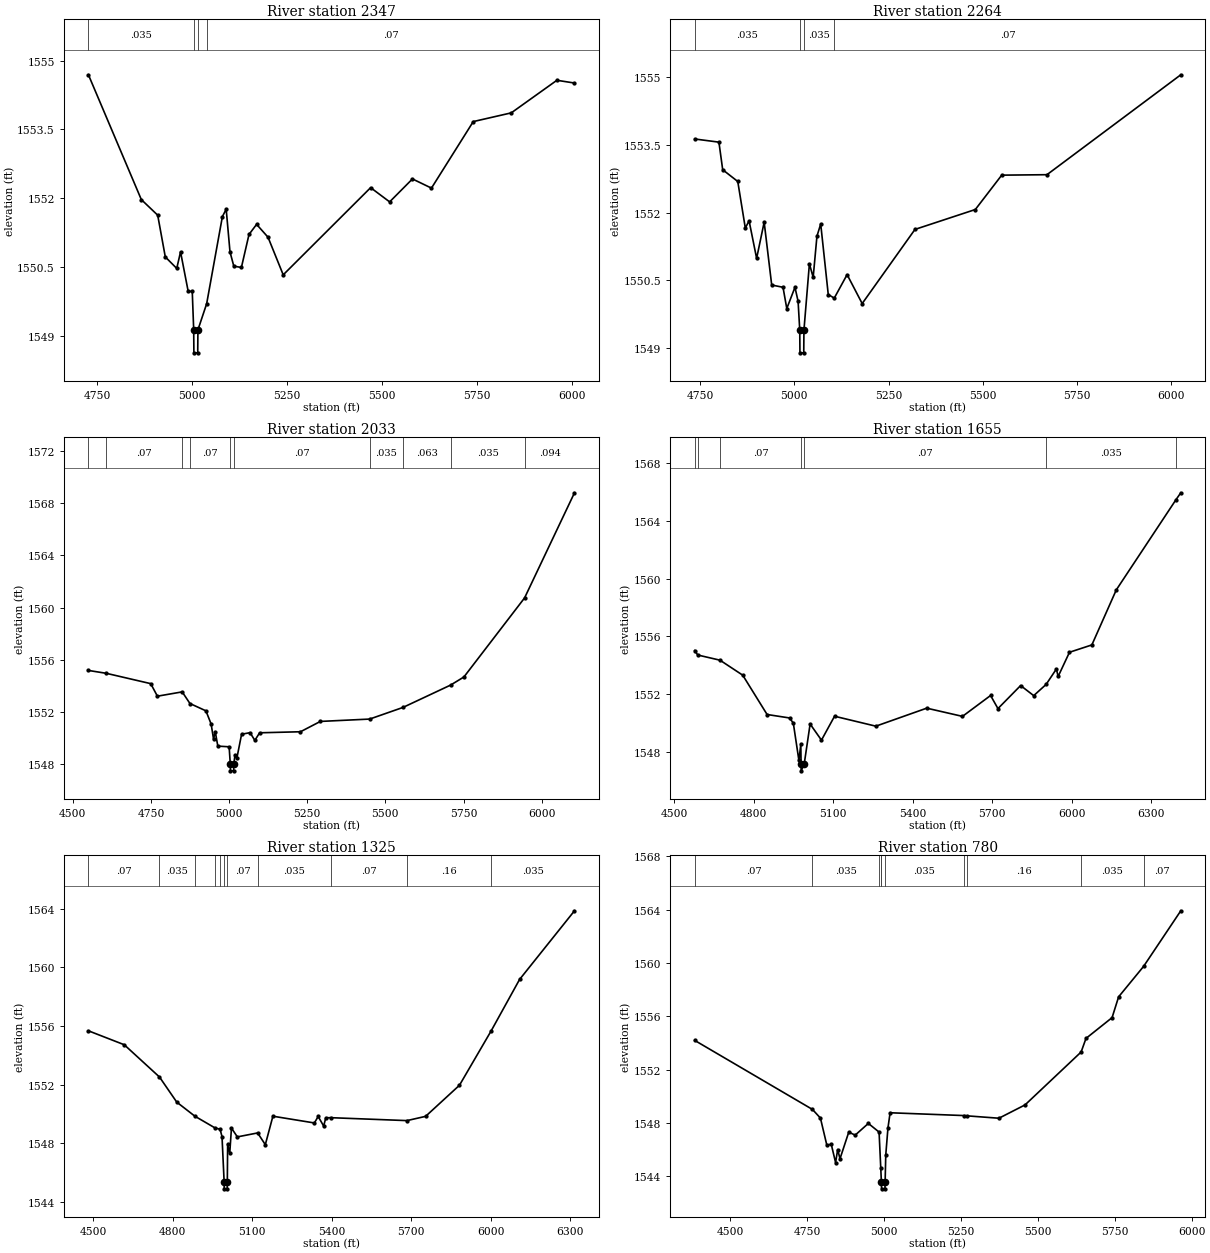
Type RM Length L Ch R = 1,2347,83,83,83
BEGIN DESCRIPTION:
Mapping XS 1dfa4f1b
END DESCRIPTION:
XS GIS Cut Line= 3
      1605759.16      6966909.72      1605779.78      6966641.70
      1605779.28      6965631.71
#Sta/Elev= 30
  4727.7 1554.69  4866.9 1551.97  4910.0 1551.63  4930.0 1550.72  4960.1 1550.47
  4970.1 1550.83  4990.2 1549.97  5000.9 1549.97  5004.7 1549.13  5005.2 1548.63
  5015.3 1548.63  5015.8 1549.13  5038.8 1549.70  5080.2 1551.60  5090.2 1551.76
  5100.2 1550.83  5110.2 1550.52  5130.2 1550.49  5150.2 1551.21  5170.2 1551.43
  5200.2 1551.15  5240.2 1550.33  5470.2 1552.23  5520.2 1551.92  5580.2 1552.42
  5630.2 1552.22  5740.2 1553.67  5840.2 1553.86  5960.2 1554.57  6006.5 1554.51
#Mann=4,-1,0
  4727.7   0.035       0  5004.7   0.035       0  5015.8   0.035       0
  5038.8    0.07       0
Bank Sta=5004.7,5015.8
Exp/Cntr=0.3,0.1

Type RM Length L Ch R = 1,2264,231,231,231
BEGIN DESCRIPTION:
Mapping XS d81b6e4c
END DESCRIPTION:
XS GIS Cut Line= 3
      1605867.67      6966902.14      1605863.33      6966639.53
      1605883.44      6965613.08
#Sta/Elev= 30
  4735.7 1553.63  4799.9 1553.56  4809.9 1552.95  4849.9 1552.69  4869.9 1551.66
  4879.9 1551.82  4899.9 1550.99  4919.9 1551.79  4939.9 1550.40  4969.9 1550.35
  4979.9 1549.88  5001.6 1550.35  5009.9 1550.04  5014.3 1549.40  5014.8 1548.90
  5024.9 1548.90  5025.4 1549.40  5039.9 1550.87  5049.9 1550.57  5059.9 1551.48
  5069.9 1551.75  5089.9 1550.19  5105.8 1550.11  5139.9 1550.63  5179.9 1549.99
  5319.9 1551.63  5480.0 1552.07  5550.0 1552.83  5670.0 1552.84  6025.0 1555.05
#Mann=4,-1,0
  4735.7   0.035       0  5014.3   0.035       0  5025.4   0.035       0
  5105.8    0.07       0
Bank Sta=5014.3,5025.4
Exp/Cntr=0.3,0.1

Type RM Length L Ch R = 1,2033,378,378,378
BEGIN DESCRIPTION:
Mapping XS aff18f6a
END DESCRIPTION:
XS GIS Cut Line= 3
      1605893.24      6967153.57      1606057.30      6966734.30
      1606645.82      6965799.44
#Sta/Elev= 30
  4550.1 1555.19  4607.4 1554.97  4749.4 1554.18  4770.8 1553.22  4850.1 1553.55
  4874.9 1552.66  4926.0 1552.10  4942.7 1551.09  4950.4 1549.94  4955.8 1550.51
  4964.1 1549.40  5000.3 1549.35  5004.0 1548.01  5004.5 1547.51  5014.6 1547.51
  5015.1 1548.01  5018.9 1548.70  5024.8 1548.46  5040.1 1550.31  5067.2 1550.43
  5082.5 1549.84  5097.8 1550.42  5228.5 1550.50  5292.1 1551.29  5449.8 1551.47
  5556.3 1552.36  5708.7 1554.07  5751.3 1554.69  5945.4 1560.74  6105.0 1568.78
#Mann=10,-1,0
  4550.1   0.035       0  4607.4    0.07       0  4850.1   0.035       0
  4874.9    0.07       0  5004.0    0.07       0  5015.1    0.07       0
  5449.8   0.035       0  5556.3   0.063       0  5708.7   0.035       0
  5945.4   0.094       0
Bank Sta=5004,5015.1
Exp/Cntr=0.3,0.1

Type RM Length L Ch R = 1,1655,330,330,330
BEGIN DESCRIPTION:
Mapping XS 1fe36a40
END DESCRIPTION:
XS GIS Cut Line= 3
      1605956.14      6967275.41      1606257.82      6966980.25
      1607329.84      6966060.13
#Sta/Elev= 30
  4577.4 1555.01  4588.7 1554.70  4672.8 1554.34  4758.6 1553.30  4850.6 1550.57
  4935.4 1550.33  4949.6 1549.97  4970.7 1547.38  4977.9 1548.51  4978.8 1547.16
  4979.3 1546.66  4990.9 1547.16  5013.0 1549.91  5055.8 1548.79  5105.2 1550.45
  5261.1 1549.76  5453.1 1551.01  5588.1 1550.44  5694.2 1551.89  5722.0 1550.98
  5807.6 1552.58  5857.0 1551.88  5903.9 1552.66  5942.6 1553.73  5949.2 1553.21
  5992.0 1554.89  6076.5 1555.40  6168.7 1559.22  6394.0 1565.48  6412.2 1565.96
#Mann=7,-1,0
  4577.4    0.07       0  4588.7   0.035       0  4672.8    0.07       0
  4978.8    0.07       0  4990.9    0.07       0  5903.9   0.035       0
  6394.0    0.07       0
Bank Sta=4978.8,4990.9
Exp/Cntr=0.3,0.1

Type RM Length L Ch R = 1,1325,545,545,545
BEGIN DESCRIPTION:
Mapping XS 23bd2f33
END DESCRIPTION:
XS GIS Cut Line= 3
      1606121.73      6967594.60      1606452.45      6967193.57
      1607465.47      6966357.63
#Sta/Elev= 30
  4482.4 1555.68  4617.6 1554.73  4750.5 1552.53  4815.6 1550.82  4884.0 1549.86
  4960.0 1549.06  4979.0 1548.97  4986.3 1548.47  4994.2 1545.41  4994.7 1544.91
  5005.8 1544.91  5006.3 1545.41  5007.5 1547.94  5015.4 1547.33  5021.9 1549.05
  5044.1 1548.45  5120.6 1548.72  5149.6 1547.92  5178.2 1549.86  5334.6 1549.40
  5348.9 1549.84  5369.7 1549.19  5377.6 1549.75  5395.9 1549.76  5683.8 1549.56
  5754.1 1549.85  5881.8 1551.97  6001.5 1555.68  6108.5 1559.18  6315.6 1563.86
#Mann=11,-1,0
  4482.4    0.07       0  4750.5   0.035       0  4884.0    0.07       0
  4960.0   0.035       0  4979.0    0.07       0  4994.2    0.07       0
  5006.3    0.07       0  5120.6   0.035       0  5395.9    0.07       0
  5683.8    0.16       0  6001.5   0.035       0
Bank Sta=4994.2,5006.3
Exp/Cntr=0.3,0.1

Type RM Length L Ch R = 1,780,430,430,430
BEGIN DESCRIPTION:
Mapping XS 152b08bc
END DESCRIPTION:
XS GIS Cut Line= 3
      1606429.02      6967677.93      1606832.65      6967214.40
      1607517.52      6966534.75
#Sta/Elev= 30
  4385.3 1554.19  4767.9 1549.01  4793.8 1548.36  4814.7 1546.32  4828.9 1546.40
  4843.1 1545.02  4849.8 1546.00  4857.4 1545.31  4885.9 1547.31  4906.7 1547.08
  4949.5 1547.96  4984.4 1547.31  4989.9 1544.58  4991.9 1543.55  4992.4 1543.05
  5003.5 1543.05  5004.0 1543.55  5006.1 1545.59  5013.2 1547.62  5020.2 1548.76
  5259.8 1548.55  5269.2 1548.53  5373.8 1548.35  5458.7 1549.35  5640.9 1553.32
  5656.7 1554.34  5741.5 1555.90  5762.7 1557.46  5843.7 1559.74  5964.8 1563.92
#Mann=10,-1,0
  4385.3    0.07       0  4767.9   0.035       0  4984.4    0.07       0
  4989.9   0.035       0  4991.9   0.035       0  5004.0   0.035       0
  5259.8    0.07       0  5269.2    0.16       0  5640.9   0.035       0
  5843.7    0.07       0
Bank Sta=4991.9,5004
Exp/Cntr=0.3,0.1

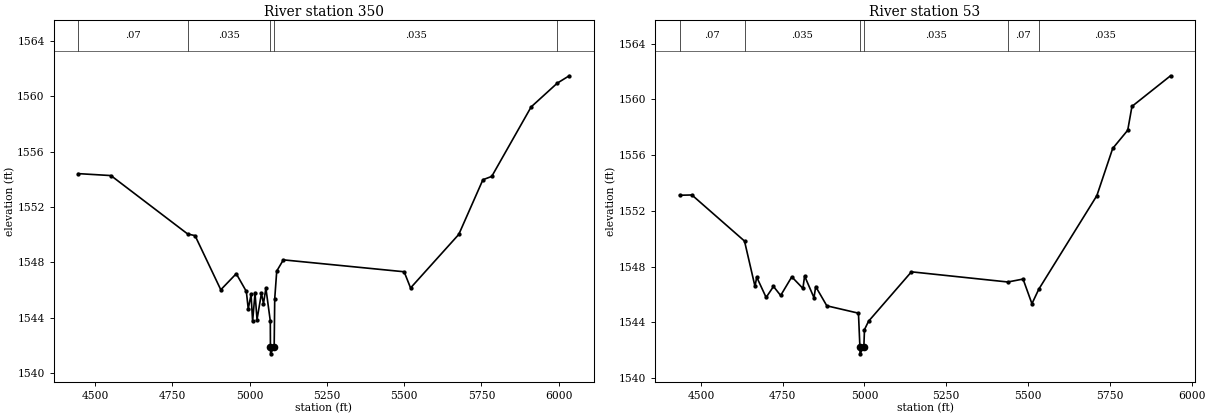
Type RM Length L Ch R = 1,350,297,297,297
BEGIN DESCRIPTION:
Mapping XS fdb08740
END DESCRIPTION:
XS GIS Cut Line= 3
      1606410.82      6967873.24      1606905.57      6967620.65
      1607569.63      6966828.99
#Sta/Elev= 30
  4445.5 1554.41  4550.8 1554.27  4799.2 1550.05  4823.1 1549.93  4906.4 1546.02
  4956.5 1547.18  4989.1 1545.90  4995.3 1544.64  5004.4 1545.68  5009.4 1543.74
  5017.2 1545.77  5023.7 1543.87  5038.0 1545.76  5044.6 1545.02  5052.4 1546.13
  5066.7 1543.76  5067.1 1541.89  5067.6 1541.39  5079.2 1541.89  5081.0 1545.37
  5087.5 1547.37  5108.9 1548.18  5499.9 1547.32  5520.7 1546.15  5676.8 1550.02
  5754.9 1553.97  5783.5 1554.21  5911.0 1559.23  5995.7 1560.95  6034.3 1561.48
#Mann=5,-1,0
  4445.5    0.07       0  4799.2   0.035       0  5067.1   0.035       0
  5079.2   0.035       0  5995.7    0.07       0
Bank Sta=5067.1,5079.2
Exp/Cntr=0.3,0.1

Type RM Length L Ch R = 1,53,0,0,0
BEGIN DESCRIPTION:
Chimney Creek 1118 1.0
END DESCRIPTION:
XS GIS Cut Line= 3
      1606559.12      6967935.76      1607102.66      6967782.27
      1607596.46      6966987.83
#Sta/Elev= 30
  4435.2 1553.12  4472.5 1553.14  4633.3 1549.83  4665.4 1546.57  4670.6 1547.24
  4699.4 1545.78  4721.9 1546.57  4743.8 1545.92  4777.8 1547.26  4811.8 1546.43
  4817.0 1547.32  4845.7 1545.76  4850.9 1546.56  4884.9 1545.18  4981.6 1544.65
  4986.0 1542.23  4986.5 1541.73  4998.1 1542.23  5000.0 1543.47  5012.4 1544.07
  5143.5 1547.62  5438.2 1546.89  5484.7 1547.10  5511.8 1545.33  5532.7 1546.37
  5710.2 1553.09  5758.6 1556.48  5804.6 1557.79  5817.5 1559.50  5935.4 1561.70
#Mann=6,-1,0
  4435.2    0.07       0  4633.3   0.035       0  4986.0   0.035       0
  4998.1   0.035       0  5438.2    0.07       0  5532.7   0.035       0
Bank Sta=4986,4998.1
Exp/Cntr=0.3,0.1

Chan Stop Cuts=-1