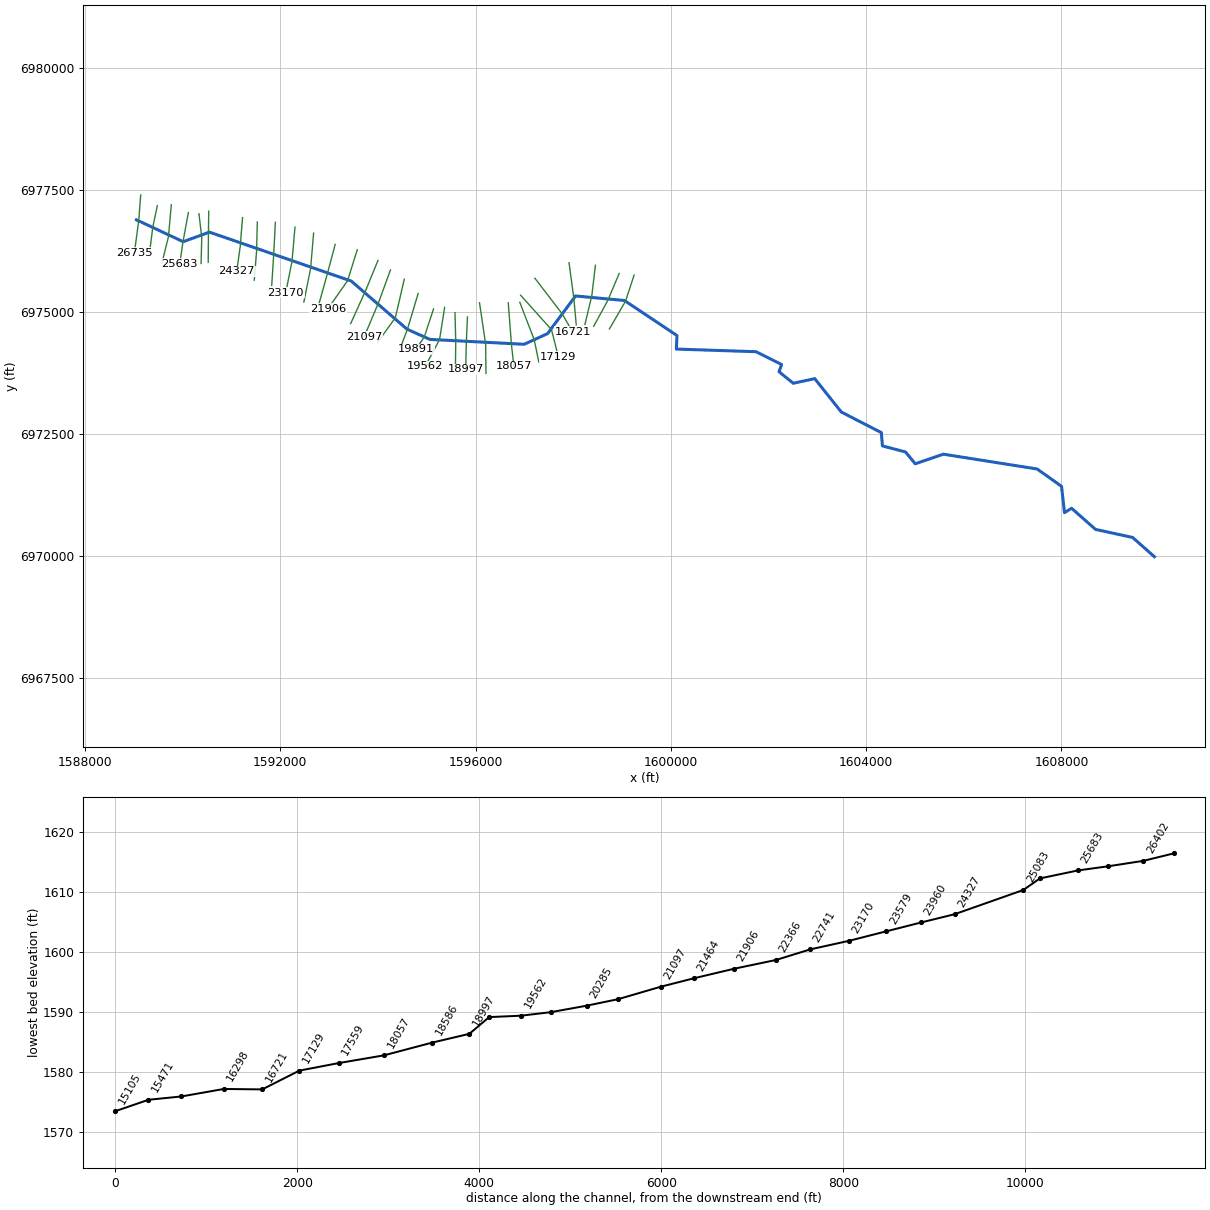
--- Chimney Creek 1121.prj (project) ---

Proj Title=Chimney Creek 1121 Base Level Engineering
Current Plan=p01
Default Exp/Contr=0.3,0.1
English Units
Geom File=g01
Flow File=f01
Plan File=p01
BEGIN DESCRIPTION:
Chimney Creek 1121
END DESCRIPTION:

--- Chimney Creek 1121.p01 (plan) ---

Plan Title=Multiple Run
Short Identifier=Multiple
Geom File=g01
Flow File=f01
Subcritical Flow
K Sum by GR= 0
Std Step Tol= 0.01
Critical Tol= 0.01
Num of Std Step Trials= 20
Max Error Tol= 0.3
Flow Tol Ratio= 0.001
Split Flow NTrial= 30
Split Flow Tol= 0.02
Split Flow Ratio= 0.02
Log Output Level= 0
Friction Slope Method= 1
Unsteady Friction Slope Method= 2
Unsteady Bridges Friction Slope Method= 1
Parabolic Critical Depth
Global Vel Dist=  1 , 1 , 1
Global Log Level= 0
CheckData=True
Encroach Param= -1, 0, 0, 0
BEGIN DESCRIPTION:
Multiple Run
END DESCRIPTION:

--- Chimney Creek 1121.f01 (steady flow) ---

Flow Title=Multiple
Number of Profiles=7
Profile Names=10-year,25-year,50-year,1pct_min,100-year,1pct_plu,500-year
River Rch & RM= Chimney Creek 11,Reach-1,26735
     192     260     314     189     378     754     553
River Rch & RM= Chimney Creek 11,Reach-1,26402
     240     328     400     242     484     965     718
River Rch & RM= Chimney Creek 11,Reach-1,23960
     414     583     723     446     890    1776    1366
River Rch & RM= Chimney Creek 11,Reach-1,15471
     441     620     770     475     948    1891    1454
River Rch & RM= Chimney Creek 11,Reach-1,11587
     493     695     863     533    1063    2121    1633
River Rch & RM= Chimney Creek 11,Reach-1,4861
     607     863    1079     669    1335    2664    2072
Boundary for River Rch & Prof#=Chimney Creek 11,Reach-1,1
Up Type=0
Dn Type=3
Dn Slope=0.005
Boundary for River Rch & Prof#=Chimney Creek 11,Reach-1,2
Up Type=0
Dn Type=3
Dn Slope=0.005
Boundary for River Rch & Prof#=Chimney Creek 11,Reach-1,3
Up Type=0
Dn Type=3
Dn Slope=0.005
Boundary for River Rch & Prof#=Chimney Creek 11,Reach-1,4
Up Type=0
Dn Type=3
Dn Slope=0.005
Boundary for River Rch & Prof#=Chimney Creek 11,Reach-1,5
Up Type=0
Dn Type=3
Dn Slope=0.005
Boundary for River Rch & Prof#=Chimney Creek 11,Reach-1,6
Up Type=0
Dn Type=3
Dn Slope=0.005
Boundary for River Rch & Prof#=Chimney Creek 11,Reach-1,7
Up Type=0
Dn Type=3
Dn Slope=0.005

--- Chimney Creek 1121.g01 (geometry) ---

Geom Title=Existing Conditions

River Reach=Chimney Creek 11,Reach-1
Reach XY= 30
      1589055.00      6976888.00      1590010.94      6976440.26
      1590548.95      6976636.42      1593453.44      6975634.24
      1594595.32      6974648.76      1595065.50      6974439.22
      1596994.50      6974339.22      1597475.09      6974557.79
      1598048.27      6975328.90      1599049.54      6975235.94
      1600125.69      6974518.38      1600113.25      6974241.07
      1601744.67      6974187.13      1602268.83      6973924.68
      1602215.76      6973777.75      1602506.76      6973540.94
      1602946.72      6973634.95      1603491.79      6972951.62
      1604311.19      6972530.15      1604333.93      6972257.79
      1604807.29      6972132.89      1605006.25      6971891.44
      1605582.31      6972088.10      1607503.53      6971784.45
      1608002.53      6971429.90      1608062.80      6970890.60
      1608208.34      6970980.40      1608698.33      6970547.30
      1609457.70      6970382.64      1609905.00      6969988.00

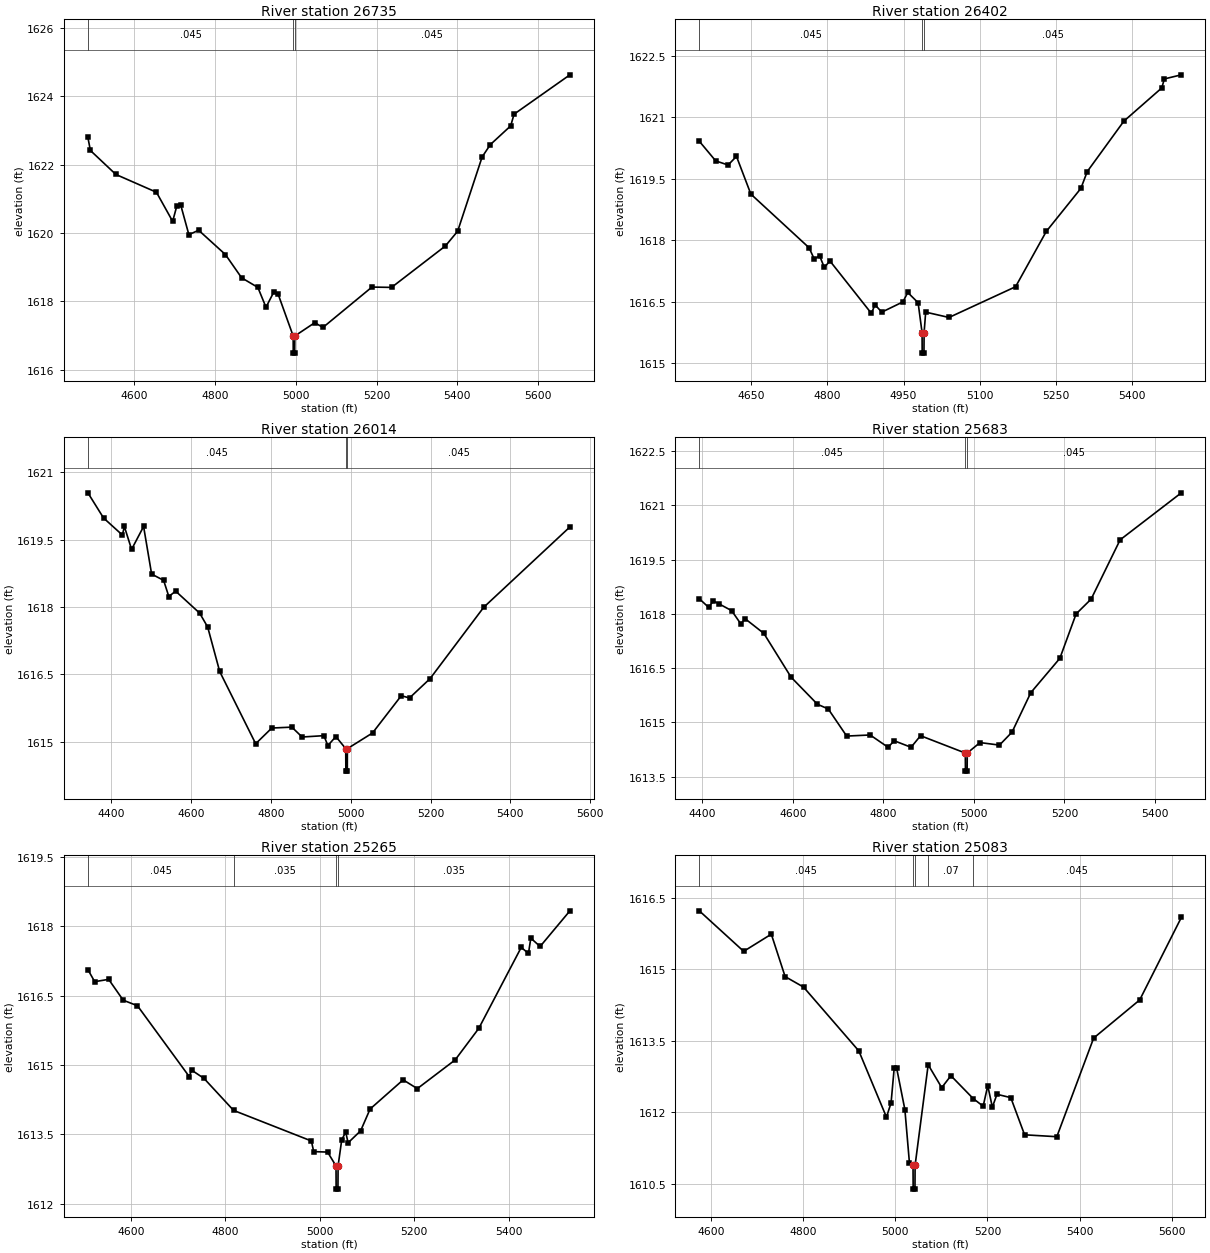
Type RM Length L Ch R = 1,26735,333,333,333
BEGIN DESCRIPTION:
Chimney Creek 1121 34.0
END DESCRIPTION:
XS GIS Cut Line= 3
      1589140.65      6977396.93      1589101.77      6976885.00
      1589012.18      6976212.95
#Sta/Elev= 30
  4486.6 1622.79  4492.8 1622.41  4555.7 1621.71  4656.0 1621.19  4696.1 1620.34
  4706.2 1620.78  4716.2 1620.81  4736.2 1619.95  4760.3 1620.08  4826.5 1619.37
  4866.6 1618.69  4906.7 1618.41  4926.8 1617.83  4946.8 1618.29  4956.9 1618.21
  4994.0 1616.99  4994.2 1616.49  4997.7 1616.49  4998.0 1616.99  5047.4 1617.38
  5067.6 1617.24  5188.7 1618.42  5237.2 1618.41  5370.2 1619.62  5400.5 1620.05
  5461.0 1622.22  5481.2 1622.58  5531.7 1623.13  5539.9 1623.47  5678.0 1624.62
#Mann=3,-1,0
  4486.6   0.045       0  4994.0   0.045       0  4998.0   0.045       0
Bank Sta=4994,4998
Exp/Cntr=0.3,0.1

Type RM Length L Ch R = 1,26402,388,388,388
BEGIN DESCRIPTION:
Mapping XS cf462c17
END DESCRIPTION:
XS GIS Cut Line= 3
      1589481.41      6977179.63      1589388.10      6976734.78
      1589325.17      6976244.33
#Sta/Elev= 30
  4547.9 1620.42  4580.2 1619.94  4604.6 1619.84  4621.1 1620.05  4649.4 1619.13
  4764.1 1617.82  4774.4 1617.54  4784.6 1617.63  4794.0 1617.34  4805.0 1617.50
  4886.7 1616.22  4893.8 1616.43  4907.2 1616.25  4948.8 1616.50  4958.3 1616.73
  4978.7 1616.48  4986.5 1615.75  4986.7 1615.25  4990.2 1615.25  4990.5 1615.75
  4993.6 1616.25  5039.5 1616.12  5170.6 1616.87  5231.1 1618.22  5299.2 1619.27
  5311.7 1619.68  5383.8 1620.91  5458.4 1621.72  5463.5 1621.94  5496.9 1622.04
#Mann=3,-1,0
  4547.9   0.045       0  4986.5   0.045       0  4990.5   0.045       0
Bank Sta=4986.5,4990.5
Exp/Cntr=0.3,0.1

Type RM Length L Ch R = 1,26014,331,331,331
BEGIN DESCRIPTION:
Mapping XS ba3bb23b
END DESCRIPTION:
XS GIS Cut Line= 3
      1589767.87      6977197.03      1589709.28      6976541.63
      1589576.91      6976007.81
#Sta/Elev= 30
  4341.3 1620.54  4380.5 1619.98  4427.7 1619.60  4432.7 1619.79  4450.8 1619.28
  4480.9 1619.79  4501.0 1618.73  4531.1 1618.59  4544.1 1618.23  4561.2 1618.35
  4621.4 1617.86  4641.5 1617.55  4671.6 1616.56  4761.8 1614.95  4802.2 1615.30
  4852.4 1615.32  4878.2 1615.10  4932.7 1615.13  4942.7 1614.91  4962.8 1615.11
  4987.5 1614.84  4987.8 1614.34  4991.4 1614.34  4991.6 1614.84  5054.6 1615.19
  5126.7 1616.02  5147.3 1615.97  5198.8 1616.40  5333.3 1617.99  5549.3 1619.78
#Mann=3,-1,0
  4341.3   0.045       0  4987.5   0.045       0  4991.6   0.045       0
Bank Sta=4987.5,4991.6
Exp/Cntr=0.3,0.1

Type RM Length L Ch R = 1,25683,418,418,418
BEGIN DESCRIPTION:
Mapping XS 2bfad36d
END DESCRIPTION:
XS GIS Cut Line= 3
      1590117.30      6977038.37      1590007.93      6976441.16
      1589940.22      6975988.03
#Sta/Elev= 30
  4393.0 1618.42  4413.7 1618.18  4423.9 1618.36  4436.3 1618.28  4464.5 1618.09
  4484.4 1617.73  4495.0 1617.86  4535.7 1617.46  4595.8 1616.25  4654.1 1615.50
  4678.0 1615.37  4718.7 1614.62  4770.6 1614.65  4810.2 1614.31  4823.8 1614.49
  4861.0 1614.31  4882.0 1614.63  4980.9 1614.15  4981.2 1613.65  4984.9 1613.65
  4985.2 1614.15  5013.4 1614.44  5056.4 1614.37  5084.2 1614.73  5125.6 1615.82
  5189.8 1616.77  5225.8 1618.00  5259.0 1618.41  5323.1 1620.05  5458.3 1621.35
#Mann=3,-1,0
  4393.0   0.045       0  4980.9   0.045       0  4985.2   0.045       0
Bank Sta=4980.9,4985.2
Exp/Cntr=0.3,0.1

Type RM Length L Ch R = 1,25265,182,182,182
BEGIN DESCRIPTION:
Mapping XS 8f0fd237
END DESCRIPTION:
XS GIS Cut Line= 3
      1590334.32      6977012.30      1590391.61      6976527.96
      1590377.72      6975994.95
#Sta/Elev= 30
  4508.8 1617.06  4523.2 1616.80  4552.8 1616.85  4583.6 1616.40  4613.8 1616.28
  4723.5 1614.75  4728.5 1614.89  4754.8 1614.71  4817.4 1614.02  4982.1 1613.36
  4987.1 1613.13  5016.5 1613.12  5034.3 1612.82  5034.6 1612.32  5038.4 1612.32
  5038.7 1612.82  5046.5 1613.39  5054.9 1613.55  5059.9 1613.32  5086.5 1613.58
  5106.5 1614.05  5176.5 1614.68  5206.5 1614.49  5286.6 1615.11  5336.6 1615.79
  5426.6 1617.54  5441.9 1617.41  5446.9 1617.74  5466.6 1617.56  5529.7 1618.33
#Mann=4,-1,0
  4508.8   0.045       0  4817.4   0.035       0  5034.3   0.035       0
  5038.7   0.035       0
Bank Sta=5034.3,5038.7
Exp/Cntr=0.3,0.1

Type RM Length L Ch R = 1,25083,756,756,756
BEGIN DESCRIPTION:
Mapping XS 187245b2
END DESCRIPTION:
XS GIS Cut Line= 3
      1590533.97      6977064.43      1590528.76      6976639.07
      1590523.55      6976017.58
#Sta/Elev= 30
  4574.1 1616.23  4670.5 1615.38  4730.5 1615.74  4760.5 1614.85  4800.5 1614.63
  4920.6 1613.29  4980.6 1611.90  4990.6 1612.20  4997.5 1612.94  5002.5 1612.94
  5020.6 1612.06  5030.6 1610.93  5038.3 1610.89  5038.6 1610.39  5042.5 1610.39
  5042.8 1610.89  5071.2 1613.00  5100.6 1612.52  5120.6 1612.77  5169.0 1612.29
  5190.6 1612.13  5200.6 1612.56  5210.6 1612.11  5220.6 1612.38  5250.6 1612.31
  5280.6 1611.53  5350.6 1611.49  5430.6 1613.56  5530.6 1614.36  5621.0 1616.09
#Mann=5,-1,0
  4574.1   0.045       0  5038.3   0.045       0  5042.8   0.045       0
  5071.2    0.07       0  5169.0   0.045       0
Bank Sta=5038.3,5042.8
Exp/Cntr=0.3,0.1

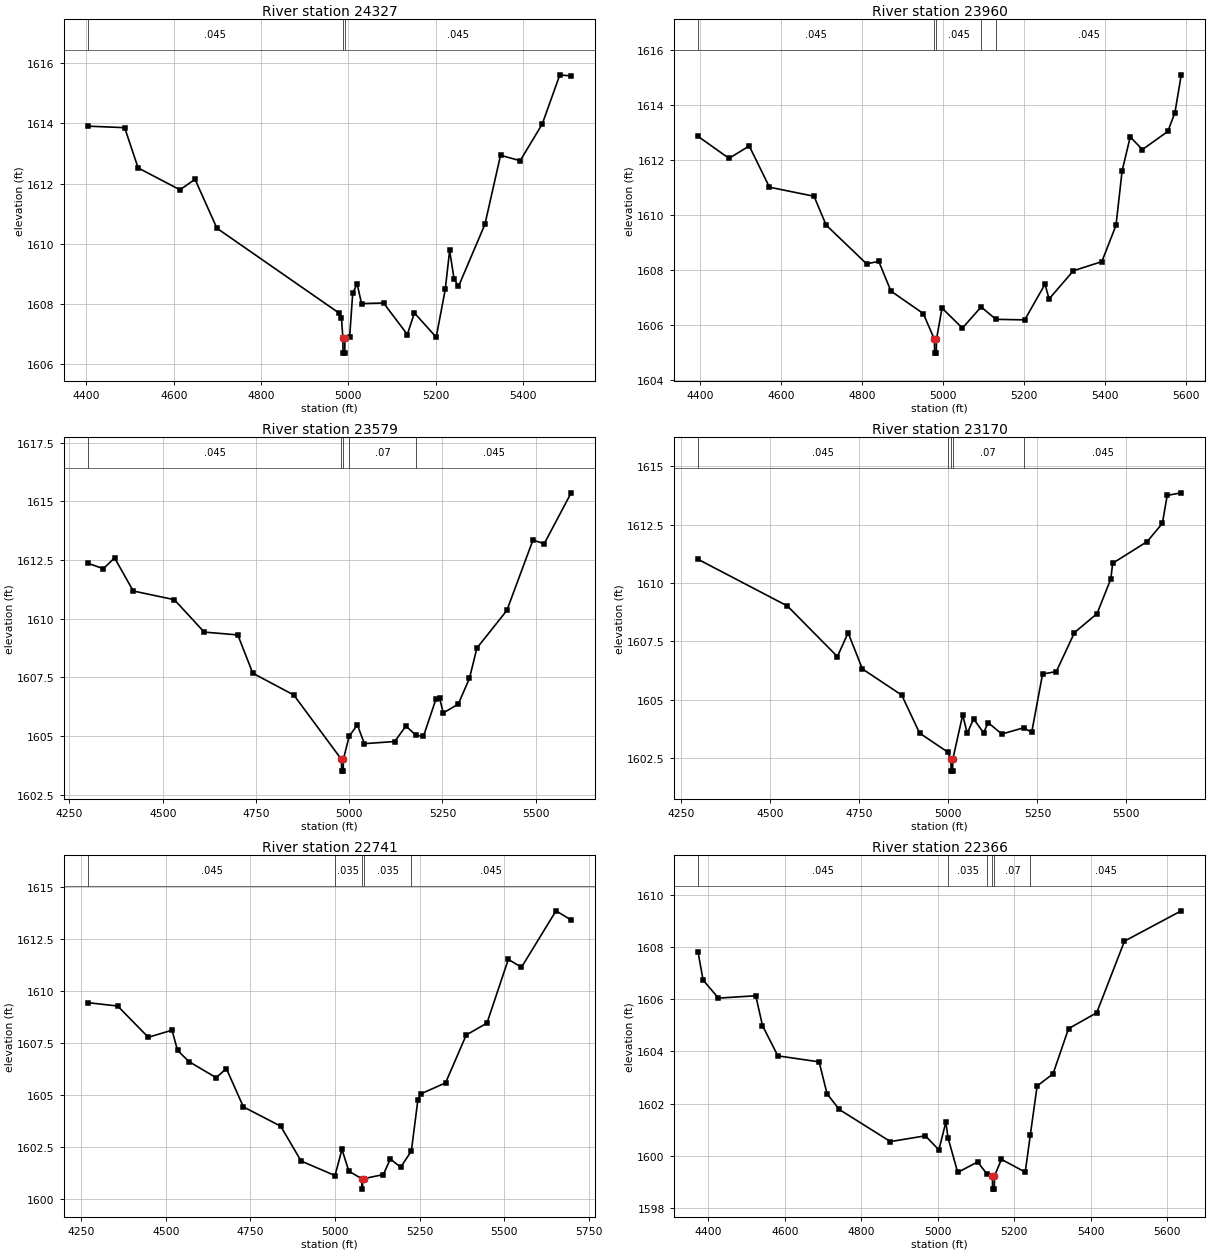
Type RM Length L Ch R = 1,24327,367,367,367
BEGIN DESCRIPTION:
Mapping XS a1dc45bc
END DESCRIPTION:
XS GIS Cut Line= 3
      1591227.20      6976932.50      1591178.59      6976336.99
      1591107.49      6975832.36
#Sta/Elev= 30
  4403.5 1613.91  4487.6 1613.86  4518.4 1612.52  4614.3 1611.79  4648.8 1612.14
  4699.0 1610.51  4979.3 1607.68  4984.3 1607.53  4987.6 1606.85  4988.0 1606.35
  4991.9 1606.35  4992.2 1606.85  5003.0 1606.88  5010.1 1608.34  5020.2 1608.66
  5030.3 1608.00  5080.8 1608.02  5135.3 1606.97  5151.4 1607.69  5201.4 1606.88
  5222.1 1608.47  5232.2 1609.77  5242.3 1608.82  5252.4 1608.57  5313.0 1610.64
  5348.8 1612.94  5393.8 1612.76  5444.3 1613.98  5484.7 1615.62  5510.6 1615.58
#Mann=3,-1,0
  4403.5   0.045       0  4987.6   0.045       0  4992.2   0.045       0
Bank Sta=4987.6,4992.2
Exp/Cntr=0.3,0.1

Type RM Length L Ch R = 1,23960,381,381,381
BEGIN DESCRIPTION:
Mapping XS 5f565515
END DESCRIPTION:
XS GIS Cut Line= 3
      1591529.63      6976844.48      1591514.00      6976240.29
      1591467.18      6975652.35
#Sta/Elev= 30
  4394.9 1612.87  4471.4 1612.07  4521.4 1612.52  4571.4 1611.02  4681.5 1610.69
  4711.5 1609.64  4811.5 1608.23  4841.5 1608.32  4871.5 1607.24  4951.6 1606.42
  4979.1 1605.48  4979.5 1604.98  4983.7 1604.98  4984.1 1605.48  4997.9 1606.62
  5048.2 1605.89  5094.5 1606.66  5131.2 1606.21  5202.2 1606.19  5252.4 1607.49
  5262.4 1606.95  5322.6 1607.98  5392.8 1608.31  5427.8 1609.63  5443.0 1611.62
  5463.0 1612.85  5493.1 1612.39  5555.9 1613.05  5573.4 1613.73  5589.1 1615.11
#Mann=5,-1,0
  4394.9   0.045       0  4979.1   0.045       0  4984.1   0.045       0
  5094.5    0.07       0  5131.2   0.045       0
Bank Sta=4979.1,4984.1
Exp/Cntr=0.3,0.1

Type RM Length L Ch R = 1,23579,409,409,409
BEGIN DESCRIPTION:
Mapping XS fb4388b5
END DESCRIPTION:
XS GIS Cut Line= 3
      1591899.42      6976839.28      1591862.96      6976141.33
      1591824.77      6975545.85
#Sta/Elev= 30
  4299.6 1612.36  4340.9 1612.13  4371.0 1612.59  4421.0 1611.18  4531.2 1610.81
  4611.3 1609.43  4701.4 1609.31  4741.5 1607.68  4851.6 1606.75  4979.3 1604.01
  4979.7 1603.51  4984.0 1603.51  4984.4 1604.01  4999.9 1604.99  5021.9 1605.48
  5040.8 1604.68  5122.1 1604.77  5152.1 1605.43  5179.6 1605.03  5199.1 1604.99
  5232.3 1606.56  5242.3 1606.62  5252.3 1605.99  5292.4 1606.36  5322.5 1607.46
  5342.5 1608.75  5422.7 1610.35  5492.8 1613.35  5522.9 1613.19  5595.2 1615.36
#Mann=5,-1,0
  4299.6   0.045       0  4979.3    0.07       0  4984.4   0.045       0
  4999.9    0.07       0  5179.6   0.045       0
Bank Sta=4979.3,4984.4
Exp/Cntr=0.3,0.1

Type RM Length L Ch R = 1,23170,429,429,429
BEGIN DESCRIPTION:
Mapping XS f69f0bfa
END DESCRIPTION:
XS GIS Cut Line= 3
      1592301.15      6976737.94      1592240.39      6976040.06
      1592111.92      6975395.97
#Sta/Elev= 30
  4296.7 1611.01  4547.6 1609.01  4688.1 1606.84  4718.2 1607.86  4758.4 1606.31
  4868.8 1605.19  4919.0 1603.56  4998.6 1602.74  5006.9 1602.43  5007.3 1601.93
  5011.7 1601.93  5012.1 1602.43  5040.1 1604.34  5052.9 1603.55  5070.7 1604.17
  5098.8 1603.57  5111.5 1604.01  5149.9 1603.52  5211.7 1603.79  5233.9 1603.59
  5264.4 1606.09  5303.1 1606.20  5354.1 1607.87  5417.4 1608.68  5456.2 1610.17
  5461.3 1610.84  5558.3 1611.77  5600.9 1612.55  5614.5 1613.75  5654.0 1613.86
#Mann=5,-1,0
  4296.7   0.045       0  4998.6    0.07       0  5006.9    0.07       0
  5012.1    0.07       0  5211.7   0.045       0
Bank Sta=5006.9,5012.1
Exp/Cntr=0.3,0.1

Type RM Length L Ch R = 1,22741,375,375,375
BEGIN DESCRIPTION:
Mapping XS c33d97ec
END DESCRIPTION:
XS GIS Cut Line= 3
      1592682.24      6976615.61      1592621.47      6975891.62
      1592482.59      6975204.15
#Sta/Elev= 30
  4269.9 1609.44  4357.8 1609.28  4448.1 1607.78  4518.4 1608.12  4534.6 1607.15
  4568.6 1606.61  4648.8 1605.84  4678.9 1606.28  4729.1 1604.44  4839.5 1603.51
  4899.7 1601.84  5000.0 1601.14  5020.5 1602.40  5040.9 1601.35  5079.1 1600.99
  5079.5 1600.49  5084.3 1600.99  5143.0 1601.19  5163.4 1601.94  5194.0 1601.54
  5225.6 1602.32  5245.0 1604.79  5253.2 1605.06  5326.6 1605.59  5387.8 1607.89
  5449.0 1608.46  5512.1 1611.52  5551.0 1611.14  5653.1 1613.85  5697.8 1613.41
#Mann=5,-1,0
  4269.9   0.045       0  5000.0   0.035       0  5079.1   0.035       0
  5084.3   0.035       0  5225.6   0.045       0
Bank Sta=5079.1,5084.3
Exp/Cntr=0.3,0.1

Type RM Length L Ch R = 1,22366,460,460,460
BEGIN DESCRIPTION:
Mapping XS cb9d4c17
END DESCRIPTION:
XS GIS Cut Line= 3
      1593123.90      6976383.80      1592962.44      6975777.90
      1592792.29      6975165.02
#Sta/Elev= 30
  4373.4 1607.80  4386.6 1606.73  4426.7 1606.04  4524.3 1606.13  4541.8 1604.99
  4582.0 1603.83  4689.9 1603.60  4710.6 1602.38  4742.4 1601.78  4876.2 1600.55
  4967.6 1600.77  5003.0 1600.23  5021.1 1601.29  5026.9 1600.69  5052.2 1599.37
  5104.1 1599.77  5129.3 1599.30  5142.9 1599.23  5143.3 1598.73  5147.9 1598.73
  5148.3 1599.23  5166.4 1599.87  5228.7 1599.38  5241.8 1600.79  5259.8 1602.68
  5301.3 1603.14  5341.8 1604.87  5415.5 1605.48  5488.1 1608.22  5636.5 1609.38
#Mann=6,-1,0
  4373.4   0.045       0  5026.9   0.035       0  5129.3    0.07       0
  5142.9   0.045       0  5148.3    0.07       0  5241.8   0.045       0
Bank Sta=5142.9,5148.3
Exp/Cntr=0.3,0.1

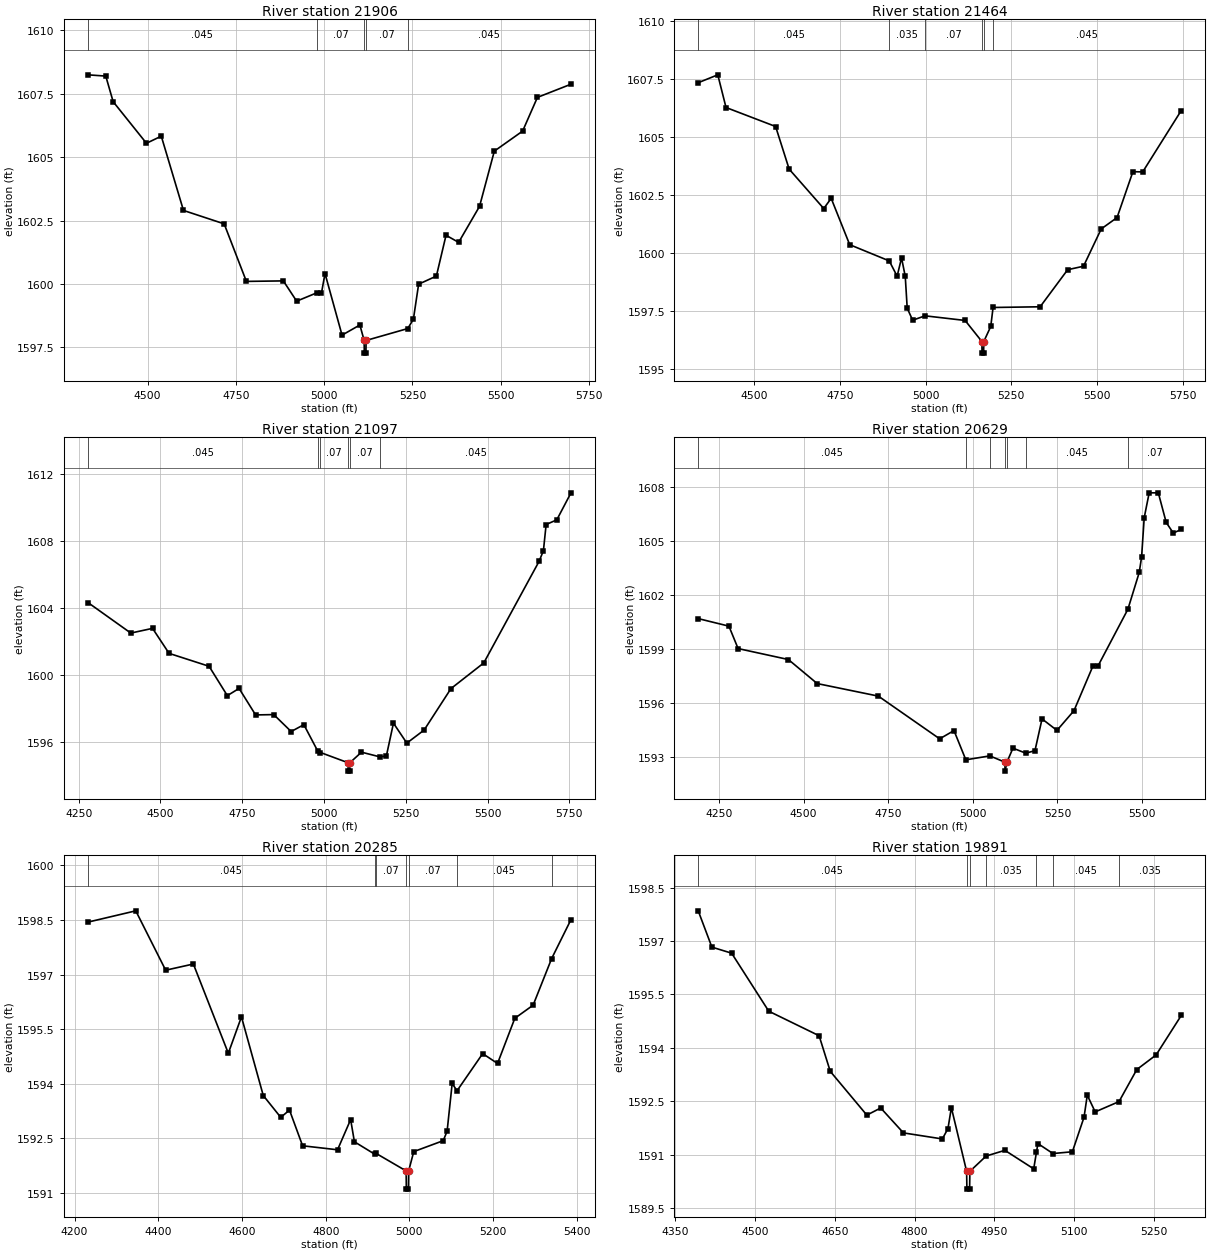
Type RM Length L Ch R = 1,21906,442,442,442
BEGIN DESCRIPTION:
Mapping XS 7a513173
END DESCRIPTION:
XS GIS Cut Line= 3
      1593577.02      6976276.16      1593377.37      6975639.02
      1592974.61      6975066.12
#Sta/Elev= 30
  4331.0 1608.25  4381.5 1608.20  4402.4 1607.19  4496.7 1605.55  4538.7 1605.83
  4601.5 1602.90  4716.8 1602.37  4779.7 1600.10  4884.4 1600.12  4922.1 1599.32
  4979.3 1599.65  4992.2 1599.63  5002.4 1600.41  5050.6 1597.98  5101.1 1598.38
  5113.2 1597.77  5113.7 1597.27  5118.3 1597.27  5118.7 1597.77  5236.8 1598.24
  5252.7 1598.61  5267.5 1599.99  5317.8 1600.31  5345.1 1601.92  5380.8 1601.64
  5440.0 1603.06  5481.9 1605.24  5562.0 1606.03  5603.9 1607.36  5699.0 1607.88
#Mann=5,-1,0
  4331.0   0.045       0  4979.3    0.07       0  5113.2    0.07       0
  5118.7    0.07       0  5236.8   0.045       0
Bank Sta=5113.2,5118.7
Exp/Cntr=0.3,0.1

Type RM Length L Ch R = 1,21464,367,367,367
BEGIN DESCRIPTION:
Mapping XS e6f76430
END DESCRIPTION:
XS GIS Cut Line= 3
      1594001.20      6976056.92      1593749.48      6975442.37
      1593442.20      6974763.58
#Sta/Elev= 30
  4336.8 1607.35  4393.9 1607.69  4417.9 1606.28  4562.6 1605.46  4602.1 1603.62
  4703.0 1601.92  4724.7 1602.36  4778.7 1600.36  4894.1 1599.66  4917.1 1599.00
  4930.0 1599.79  4940.8 1598.99  4946.5 1597.62  4962.4 1597.10  4998.5 1597.29
  5115.4 1597.09  5164.4 1596.18  5164.8 1595.68  5169.4 1595.68  5169.9 1596.18
  5190.2 1596.83  5197.0 1597.65  5334.3 1597.68  5414.6 1599.28  5460.8 1599.43
  5512.5 1601.04  5558.7 1601.53  5604.9 1603.51  5633.5 1603.50  5746.0 1606.15
#Mann=6,-1,0
  4336.8   0.045       0  4894.1   0.035       0  4998.5    0.07       0
  5164.4    0.07       0  5169.9    0.07       0  5197.0   0.045       0
Bank Sta=5164.4,5169.9
Exp/Cntr=0.3,0.1

Type RM Length L Ch R = 1,21097,468,468,468
BEGIN DESCRIPTION:
Mapping XS 614e2758
END DESCRIPTION:
XS GIS Cut Line= 3
      1594256.43      6975861.67      1594009.03      6975182.39
      1593716.08      6974487.99
#Sta/Elev= 30
  4278.3 1604.31  4409.3 1602.49  4475.8 1602.77  4526.3 1601.28  4648.6 1600.51
  4704.4 1598.76  4740.3 1599.19  4790.8 1597.61  4846.3 1597.63  4899.5 1596.62
  4938.3 1597.03  4980.1 1595.48  4989.1 1595.37  5073.5 1594.76  5073.9 1594.26
  5078.5 1594.26  5079.0 1594.76  5114.5 1595.39  5170.8 1595.11  5190.5 1595.16
  5212.2 1597.12  5253.1 1595.93  5306.0 1596.71  5388.0 1599.18  5488.3 1600.71
  5657.2 1606.76  5670.6 1607.40  5678.9 1608.96  5711.5 1609.24  5754.9 1610.85
#Mann=6,-1,0
  4278.3   0.045       0  4980.1   0.035       0  4989.1    0.07       0
  5073.5    0.07       0  5079.0    0.07       0  5170.8   0.045       0
Bank Sta=5073.5,5079
Exp/Cntr=0.3,0.1

Type RM Length L Ch R = 1,20629,344,344,344
BEGIN DESCRIPTION:
Mapping XS e69e02e1
END DESCRIPTION:
XS GIS Cut Line= 3
      1594540.19      6975672.75      1594356.16      6974881.09
      1593996.86      6974382.92
#Sta/Elev= 30
  4188.7 1600.69  4279.4 1600.27  4306.5 1599.02  4455.0 1598.41  4540.2 1597.07
  4720.9 1596.37  4902.0 1593.99  4944.3 1594.45  4979.3 1592.82  5050.1 1593.04
  5094.7 1592.69  5095.2 1592.19  5100.6 1592.69  5118.5 1593.47  5156.4 1593.19
  5183.5 1593.33  5204.4 1595.10  5248.5 1594.46  5298.8 1595.56  5355.3 1598.07
  5370.0 1598.06  5458.0 1601.21  5491.5 1603.26  5498.5 1604.12  5506.2 1606.31
  5520.9 1607.70  5547.9 1607.70  5571.2 1606.05  5592.1 1605.46  5615.7 1605.66
#Mann=7,-1,0
  4188.7   0.045       0  4979.3   0.035       0  5050.1    0.07       0
  5094.7   0.035       0  5100.6    0.07       0  5156.4   0.045       0
  5458.0    0.07       0
Bank Sta=5094.7,5100.6
Exp/Cntr=0.3,0.1

Type RM Length L Ch R = 1,20285,394,394,394
BEGIN DESCRIPTION:
Mapping XS 212d2ecb
END DESCRIPTION:
XS GIS Cut Line= 3
      1594823.75      6975379.32      1594603.27      6974643.24
      1594466.28      6974282.57
#Sta/Elev= 30
  4231.9 1598.44  4346.2 1598.75  4417.6 1597.12  4483.8 1597.29  4567.3 1594.84
  4598.7 1595.84  4650.8 1593.68  4692.6 1593.08  4713.5 1593.28  4744.8 1592.30
  4828.3 1592.19  4859.6 1593.02  4868.6 1592.41  4917.0 1592.07  4919.0 1592.10
  4992.2 1591.61  4992.7 1591.11  4997.7 1591.11  4998.2 1591.61  5010.4 1592.14
  5080.8 1592.44  5090.1 1592.70  5102.2 1594.01  5113.8 1593.81  5175.1 1594.83
  5210.6 1594.56  5251.9 1595.80  5295.6 1596.16  5339.9 1597.44  5386.1 1598.51
#Mann=7,-1,0
  4231.9   0.045       0  4917.0   0.035       0  4919.0    0.07       0
  4992.2    0.07       0  4998.2    0.07       0  5113.8   0.045       0
  5339.9   0.035       0
Bank Sta=4992.2,4998.2
Exp/Cntr=0.3,0.1

Type RM Length L Ch R = 1,19891,329,329,329
BEGIN DESCRIPTION:
Mapping XS 5ccb9992
END DESCRIPTION:
XS GIS Cut Line= 3
      1595139.21      6975063.91      1594949.97      6974489.25
      1594779.07      6974238.94
#Sta/Elev= 30
  4393.4 1597.85  4419.1 1596.83  4456.2 1596.66  4526.0 1595.03  4620.7 1594.34
  4641.6 1593.34  4710.4 1592.11  4736.5 1592.31  4779.2 1591.61  4852.3 1591.44
  4862.9 1591.73  4869.3 1592.32  4898.0 1590.53  4898.5 1590.03  4903.6 1590.03
  4904.1 1590.53  4934.7 1590.96  4969.9 1591.12  5024.1 1590.60  5029.3 1591.07
  5032.0 1591.31  5060.3 1591.03  5096.8 1591.08  5118.7 1592.05  5124.8 1592.67
  5139.7 1592.20  5184.5 1592.49  5217.9 1593.39  5254.2 1593.80  5301.5 1594.91
#Mann=7,-1,0
  4393.4   0.045       0  4898.0   0.035       0  4904.1   0.045       0
  4934.7   0.035       0  5029.3    0.07       0  5060.3   0.045       0
  5184.5   0.035       0
Bank Sta=4898,4904.1
Exp/Cntr=0.3,0.1

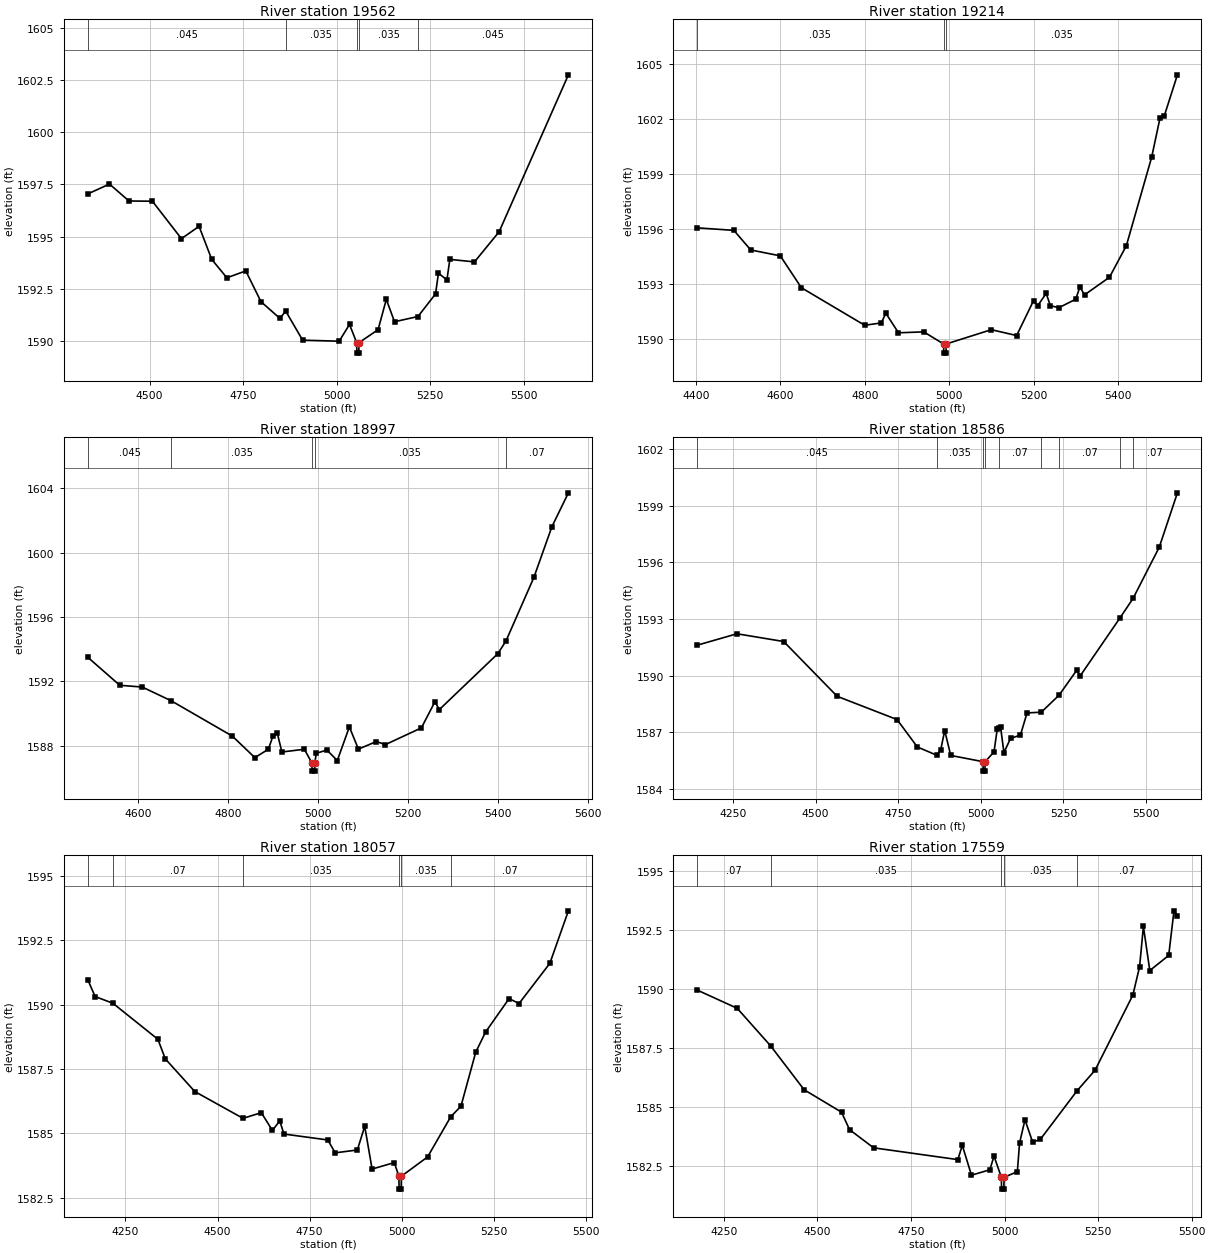
Type RM Length L Ch R = 1,19562,348,348,348
BEGIN DESCRIPTION:
Mapping XS 318a739a
END DESCRIPTION:
XS GIS Cut Line= 3
      1595366.64      6975095.17      1595262.47      6974435.43
      1594971.55      6973891.68
#Sta/Elev= 30
  4334.7 1597.05  4392.6 1597.52  4444.8 1596.71  4507.3 1596.70  4584.9 1594.91
  4632.1 1595.50  4665.9 1593.92  4706.4 1593.04  4757.0 1593.37  4797.5 1591.90
  4848.2 1591.10  4863.6 1591.45  4908.9 1590.06  5006.6 1590.01  5034.2 1590.81
  5053.4 1589.94  5053.9 1589.44  5059.0 1589.44  5059.5 1589.94  5110.6 1590.56
  5132.6 1592.01  5154.5 1590.94  5217.2 1591.19  5264.2 1592.27  5271.9 1593.26
  5294.6 1592.94  5302.4 1593.92  5368.3 1593.80  5434.1 1595.24  5619.3 1602.74
#Mann=5,-1,0
  4334.7   0.045       0  4863.6   0.035       0  5053.4   0.035       0
  5059.5   0.035       0  5217.2   0.045       0
Bank Sta=5053.4,5059.5
Exp/Cntr=0.3,0.1

Type RM Length L Ch R = 1,19214,217,217,217
BEGIN DESCRIPTION:
Mapping XS 7d97c11e
END DESCRIPTION:
XS GIS Cut Line= 3
      1595578.44      6974985.76      1595594.07      6974388.55
      1595587.12      6973846.91
#Sta/Elev= 30
  4401.9 1596.05  4489.7 1595.91  4529.7 1594.84  4599.7 1594.52  4649.7 1592.78
  4799.8 1590.73  4839.3 1590.86  4849.8 1591.39  4879.8 1590.32  4939.8 1590.37
  4986.7 1589.71  4987.2 1589.21  4992.5 1589.21  4993.0 1589.71  5099.9 1590.49
  5159.9 1590.17  5199.9 1592.07  5209.9 1591.80  5229.9 1592.47  5239.9 1591.80
  5259.9 1591.69  5299.9 1592.15  5309.9 1592.82  5320.8 1592.39  5379.9 1593.35
  5419.9 1595.07  5479.9 1599.90  5499.9 1602.06  5509.9 1602.16  5541.0 1604.40
#Mann=3,-1,0
  4401.9   0.035       0  4986.7   0.035       0  4993.0   0.035       0
Bank Sta=4986.7,4993
Exp/Cntr=0.3,0.1

Type RM Length L Ch R = 1,18997,411,411,411
BEGIN DESCRIPTION:
Mapping XS 5b78de25
END DESCRIPTION:
XS GIS Cut Line= 3
      1595833.65      6974898.93      1595811.08      6974390.29
      1595797.24      6973831.30
#Sta/Elev= 30
  4488.7 1593.50  4559.7 1591.76  4609.7 1591.65  4674.4 1590.79  4809.9 1588.60
  4860.0 1587.26  4890.0 1587.78  4900.0 1588.58  4910.0 1588.77  4920.1 1587.61
  4970.1 1587.78  4986.9 1586.92  4987.4 1586.42  4992.8 1586.42  4993.3 1586.92
  4996.5 1587.53  5020.1 1587.73  5043.3 1587.08  5070.1 1589.17  5090.2 1587.79
  5130.2 1588.26  5150.2 1588.07  5230.2 1589.11  5260.2 1590.73  5270.2 1590.25
  5400.3 1593.73  5418.3 1594.52  5480.3 1598.47  5520.3 1601.62  5557.0 1603.73
#Mann=5,-1,0
  4488.7   0.045       0  4674.4   0.035       0  4986.9   0.035       0
  4993.3   0.035       0  5418.3    0.07       0
Bank Sta=4986.9,4993.3
Exp/Cntr=0.3,0.1

Type RM Length L Ch R = 1,18586,529,529,529
BEGIN DESCRIPTION:
Mapping XS db1fd13a
END DESCRIPTION:
XS GIS Cut Line= 3
      1596080.91      6975188.18      1596206.77      6974335.35
      1596213.28      6973742.96
#Sta/Elev= 30
  4140.6 1591.61  4262.1 1592.22  4403.5 1591.81  4565.3 1588.91  4746.5 1587.68
  4807.9 1586.23  4866.8 1585.79  4878.7 1586.08  4890.8 1587.10  4909.0 1585.78
  5006.8 1585.45  5007.3 1584.95  5012.7 1584.95  5013.2 1585.45  5040.0 1585.97
  5050.0 1587.20  5056.0 1587.24  5060.0 1587.27  5070.0 1585.93  5090.0 1586.68
  5120.0 1586.86  5140.0 1588.03  5183.2 1588.07  5236.9 1588.97  5290.0 1590.28
  5300.8 1589.99  5421.7 1593.07  5460.8 1594.09  5540.1 1596.80  5595.1 1599.68
#Mann=9,-1,0
  4140.6   0.045       0  4866.8   0.035       0  5006.8   0.035       0
  5013.2   0.035       0  5056.0    0.07       0  5183.2   0.035       0
  5236.9    0.07       0  5421.7   0.035       0  5460.8    0.07       0
Bank Sta=5006.8,5013.2
Exp/Cntr=0.3,0.1

Type RM Length L Ch R = 1,18057,498,498,498
BEGIN DESCRIPTION:
Mapping XS 7fe95e41
END DESCRIPTION:
XS GIS Cut Line= 3
      1596669.44      6975187.77      1596734.55      6974341.42
      1596784.46      6973887.91
#Sta/Elev= 30
  4147.7 1590.96  4167.5 1590.31  4215.8 1590.05  4338.0 1588.65  4358.1 1587.89
  4438.3 1586.62  4569.2 1585.58  4618.9 1585.80  4648.9 1585.11  4669.0 1585.48
  4680.3 1584.97  4799.4 1584.74  4819.5 1584.24  4879.6 1584.35  4899.7 1585.27
  4919.7 1583.61  4979.9 1583.86  4992.5 1583.33  4993.0 1582.83  4998.6 1582.83
  4999.1 1583.33  5070.4 1584.08  5133.2 1585.64  5161.0 1586.05  5201.2 1588.15
  5227.8 1588.93  5291.7 1590.23  5318.8 1590.04  5402.4 1591.60  5452.8 1593.64
#Mann=6,-1,0
  4147.7   0.045       0  4215.8    0.07       0  4569.2   0.035       0
  4992.5   0.035       0  4999.1   0.035       0  5133.2    0.07       0
Bank Sta=4992.5,4999.1
Exp/Cntr=0.3,0.1

Type RM Length L Ch R = 1,17559,430,430,430
BEGIN DESCRIPTION:
Mapping XS 1cd26b28
END DESCRIPTION:
XS GIS Cut Line= 3
      1596906.00      6975198.61      1597201.13      6974434.74
      1597294.45      6973978.99
#Sta/Elev= 30
  4177.9 1589.98  4285.8 1589.20  4375.0 1587.61  4464.6 1585.75  4564.5 1584.80
  4585.9 1584.06  4650.2 1583.29  4875.4 1582.79  4887.1 1583.40  4911.7 1582.13
  4960.9 1582.36  4971.9 1582.94  4991.6 1582.04  4992.1 1581.54  4998.3 1581.54
  4998.8 1582.04  5034.3 1582.28  5040.2 1583.49  5054.7 1584.48  5075.1 1583.53
  5095.8 1583.65  5194.0 1585.71  5242.0 1586.58  5342.9 1589.76  5360.9 1590.96
  5371.1 1592.67  5388.2 1590.80  5438.7 1591.44  5452.8 1593.33  5462.0 1593.12
#Mann=5,-1,0
  4177.9    0.07       0  4375.0   0.035       0  4991.6   0.035       0
  4998.8   0.035       0  5194.0    0.07       0
Bank Sta=4991.6,4998.8
Exp/Cntr=0.3,0.1

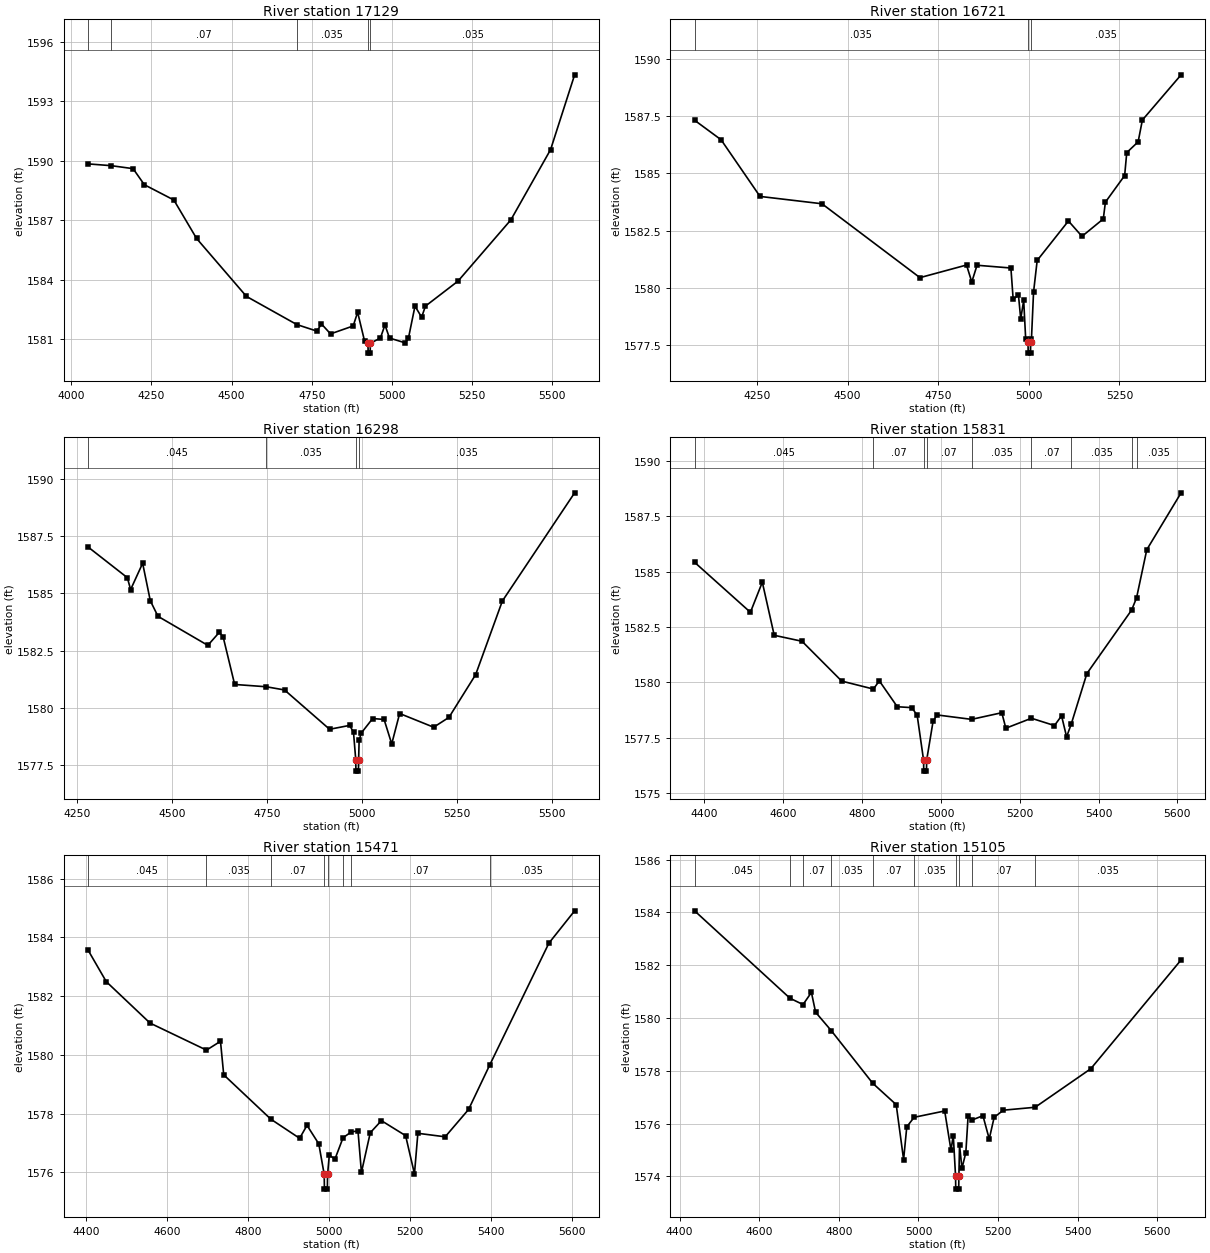
Type RM Length L Ch R = 1,17129,408,408,408
BEGIN DESCRIPTION:
Mapping XS 4e78980e
END DESCRIPTION:
XS GIS Cut Line= 5
      1596923.32      6975344.06      1597554.86      6974638.73
      1597691.58      6974100.54      1597693.75      6974096.20
      1597693.75      6974085.39
#Sta/Elev= 30
  4052.5 1589.83  4124.6 1589.74  4192.8 1589.59  4227.9 1588.78  4319.9 1588.01
  4390.9 1586.07  4546.4 1583.15  4703.6 1581.73  4766.2 1581.40  4780.4 1581.76
  4808.8 1581.26  4879.4 1581.66  4893.3 1582.35  4915.0 1580.89  4925.6 1580.79
  4926.1 1580.29  4932.4 1580.29  4932.9 1580.79  4964.3 1581.05  4978.5 1581.71
  4992.7 1581.05  5041.3 1580.81  5051.6 1581.03  5072.2 1582.66  5092.9 1582.10
  5104.8 1582.66  5206.4 1583.92  5371.4 1587.01  5495.2 1590.55  5570.2 1594.32
#Mann=5,-1,0
  4052.5   0.035       0  4124.6    0.07       0  4703.6   0.035       0
  4925.6   0.035       0  4932.9   0.035       0
Bank Sta=4925.6,4932.9
Exp/Cntr=0.3,0.1

Type RM Length L Ch R = 1,16721,423,423,423
BEGIN DESCRIPTION:
Mapping XS 7c5595e9
END DESCRIPTION:
XS GIS Cut Line= 3
      1597215.74      6975691.25      1597773.47      6974964.25
      1597986.13      6974595.35
#Sta/Elev= 30
  4078.0 1587.31  4151.1 1586.46  4258.5 1583.99  4429.4 1583.67  4699.7 1580.45
  4828.2 1581.00  4842.7 1580.26  4857.2 1580.99  4950.6 1580.87  4956.9 1579.50
  4971.4 1579.70  4977.7 1578.65  4985.9 1579.46  4991.4 1577.77  4997.8 1577.66
  4998.3 1577.16  5004.7 1577.16  5005.2 1577.66  5007.3 1577.77  5013.1 1579.82
  5023.1 1581.20  5109.3 1582.92  5146.7 1582.25  5205.5 1583.01  5211.3 1583.74
  5264.4 1584.90  5270.2 1585.90  5301.6 1586.37  5313.3 1587.32  5420.1 1589.29
#Mann=3,-1,0
  4078.0   0.035       0  4997.8   0.035       0  5005.2   0.035       0
Bank Sta=4997.8,5005.2
Exp/Cntr=0.3,0.1

Type RM Length L Ch R = 1,16298,467,467,467
BEGIN DESCRIPTION:
Mapping XS 216d6578
END DESCRIPTION:
XS GIS Cut Line= 3
      1597914.53      6976010.24      1598012.18      6975287.61
      1598062.09      6974738.57
#Sta/Elev= 30
  4278.3 1587.03  4381.5 1585.69  4390.2 1585.17  4421.8 1586.32  4442.0 1584.68
  4462.2 1584.00  4593.4 1582.73  4623.6 1583.30  4633.7 1583.10  4664.0 1581.02
  4746.9 1580.92  4795.2 1580.78  4913.9 1579.06  4966.7 1579.23  4976.8 1578.93
  4982.7 1577.73  4983.2 1577.23  4989.8 1577.23  4990.3 1577.73  4991.6 1578.57
  4997.0 1578.89  5027.2 1579.53  5057.3 1579.49  5077.4 1578.42  5098.2 1579.75
  5187.8 1579.15  5228.0 1579.58  5298.3 1581.45  5368.6 1584.67  5558.8 1589.40
#Mann=4,-1,0
  4278.3   0.045       0  4746.9   0.035       0  4982.7   0.035       0
  4990.3   0.035       0
Bank Sta=4982.7,4990.3
Exp/Cntr=0.3,0.1

Type RM Length L Ch R = 1,15831,360,360,360
BEGIN DESCRIPTION:
Mapping XS ef796754
END DESCRIPTION:
XS GIS Cut Line= 3
      1598455.47      6975958.60      1598381.68      6975340.12
      1598240.62      6974745.49
#Sta/Elev= 30
  4375.3 1585.42  4516.9 1583.16  4547.1 1584.52  4577.3 1582.12  4647.8 1581.85
  4748.5 1580.05  4828.8 1579.69  4843.9 1580.06  4889.5 1578.89  4926.4 1578.85
  4939.9 1578.50  4956.1 1576.48  4956.6 1575.98  4963.5 1575.98  4964.0 1576.48
  4980.2 1578.23  4990.2 1578.52  5077.8 1578.32  5154.5 1578.62  5164.8 1577.92
  5229.7 1578.37  5288.1 1578.04  5306.1 1578.48  5318.9 1577.53  5330.9 1578.12
  5370.3 1580.39  5483.8 1583.26  5496.3 1583.81  5522.3 1585.99  5609.3 1588.56
#Mann=9,-1,0
  4375.3   0.045       0  4828.8    0.07       0  4956.1    0.07       0
  4964.0    0.07       0  5077.8   0.035       0  5229.7    0.07       0
  5330.9   0.035       0  5483.8    0.07       0  5496.3   0.035       0
Bank Sta=4956.1,4964
Exp/Cntr=0.3,0.1

Type RM Length L Ch R = 1,15471,366,366,366
BEGIN DESCRIPTION:
Mapping XS e524754e
END DESCRIPTION:
XS GIS Cut Line= 3
      1598941.59      6975789.36      1598709.37      6975240.30
      1598419.28      6974707.73
#Sta/Elev= 30
  4404.3 1583.56  4449.2 1582.49  4557.4 1581.08  4696.9 1580.16  4731.5 1580.46
  4739.5 1579.32  4856.0 1577.81  4927.1 1577.16  4945.4 1577.60  4974.5 1576.97
  4987.9 1575.93  4988.4 1575.43  4995.7 1575.43  4996.2 1575.93  5000.5 1576.59
  5014.4 1576.45  5034.5 1577.18  5055.2 1577.38  5071.4 1577.41  5079.9 1576.00
  5101.8 1577.35  5129.3 1577.76  5189.1 1577.25  5211.0 1575.95  5219.4 1577.33
  5286.9 1577.21  5344.7 1578.14  5396.9 1579.65  5543.3 1583.80  5606.9 1584.90
#Mann=8,-1,0
  4404.3   0.045       0  4696.9   0.035       0  4856.0    0.07       0
  4987.9    0.07       0  4996.2    0.07       0  5034.5   0.035       0
  5055.2    0.07       0  5396.9   0.035       0
Bank Sta=4987.9,4996.2
Exp/Cntr=0.3,0.1

Type RM Length L Ch R = 1,15105,554,554,554
BEGIN DESCRIPTION:
Mapping XS a3fe792c
END DESCRIPTION:
XS GIS Cut Line= 3
      1599247.56      6975756.75      1599071.79      6975222.93
      1598740.75      6974651.74
#Sta/Elev= 30
  4437.5 1584.06  4677.1 1580.75  4709.9 1580.51  4731.0 1580.97  4741.5 1580.22
  4781.0 1579.52  4885.0 1577.53  4944.0 1576.72  4962.6 1574.64  4970.6 1575.88
  4989.0 1576.24  5065.8 1576.48  5081.6 1575.00  5087.4 1575.55  5093.1 1574.02
  5093.6 1573.52  5101.0 1573.52  5101.5 1574.02  5103.1 1575.19  5109.2 1574.31
  5118.9 1574.90  5124.7 1576.30  5133.2 1576.13  5161.9 1576.30  5177.7 1575.42
  5190.1 1576.24  5213.3 1576.51  5293.0 1576.62  5432.9 1578.08  5659.7 1582.20
#Mann=10,-1,0
  4437.5   0.045       0  4677.1   0.035       0  4709.9    0.07       0
  4781.0   0.035       0  4885.0    0.07       0  4989.0   0.035       0
  5093.1   0.035       0  5101.5   0.035       0  5133.2    0.07       0
  5293.0   0.035       0
Bank Sta=5093.1,5101.5
Exp/Cntr=0.3,0.1