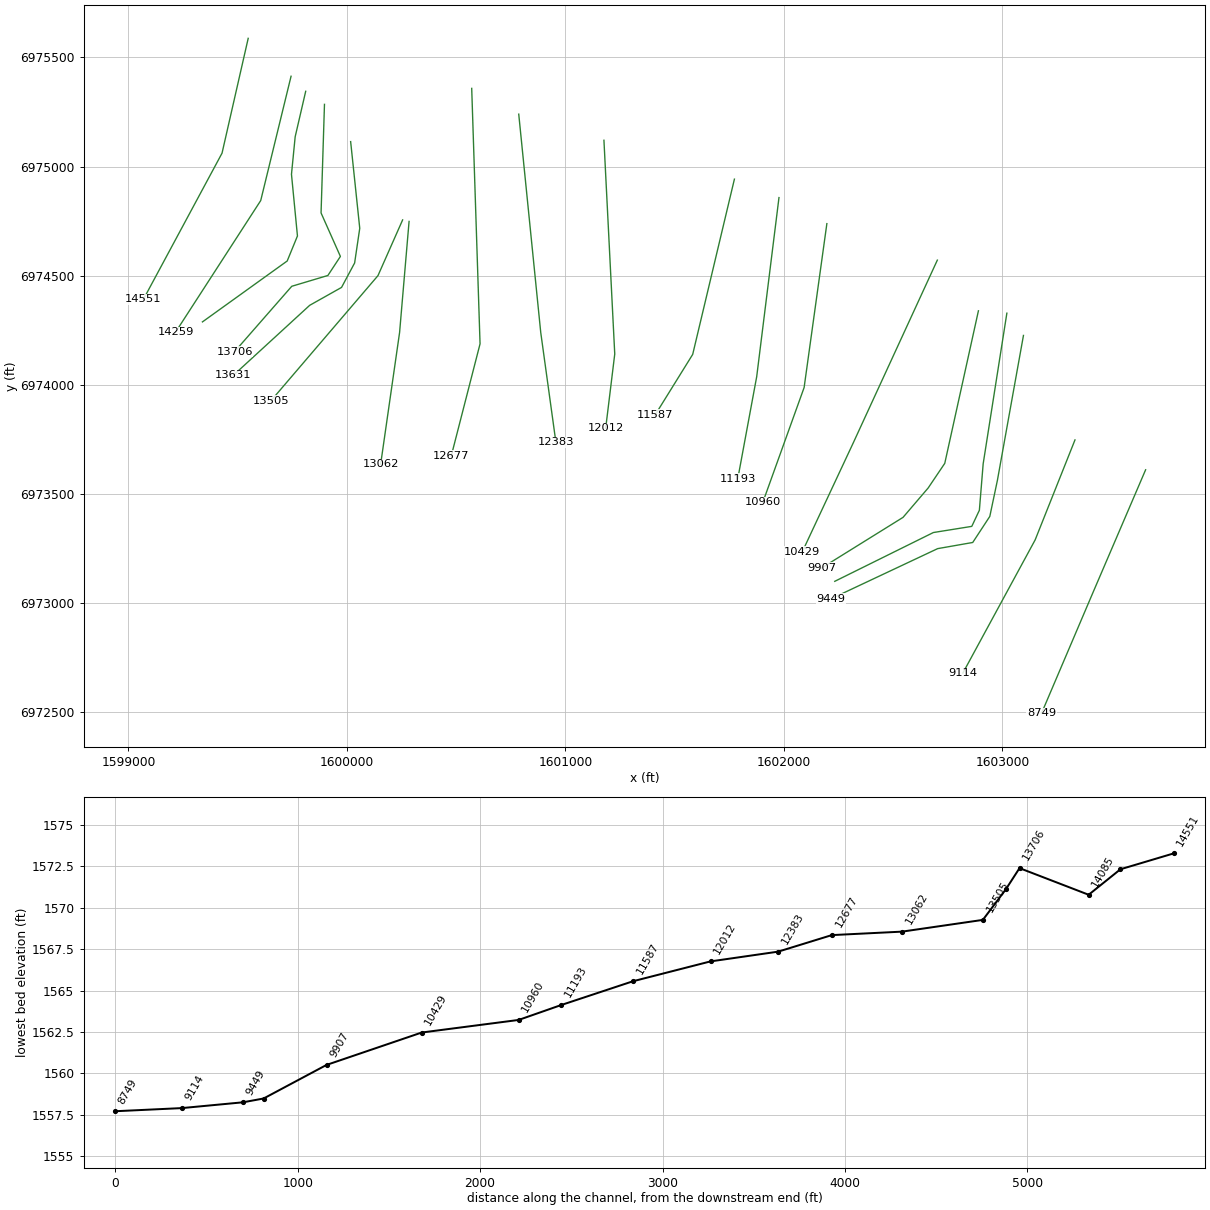
HEC-RAS study Chimney Creek 1121.prj: Chimney Creek 1121 Base Level Engineering

--- Chimney Creek 1121.g01 (geometry) --- (continued)

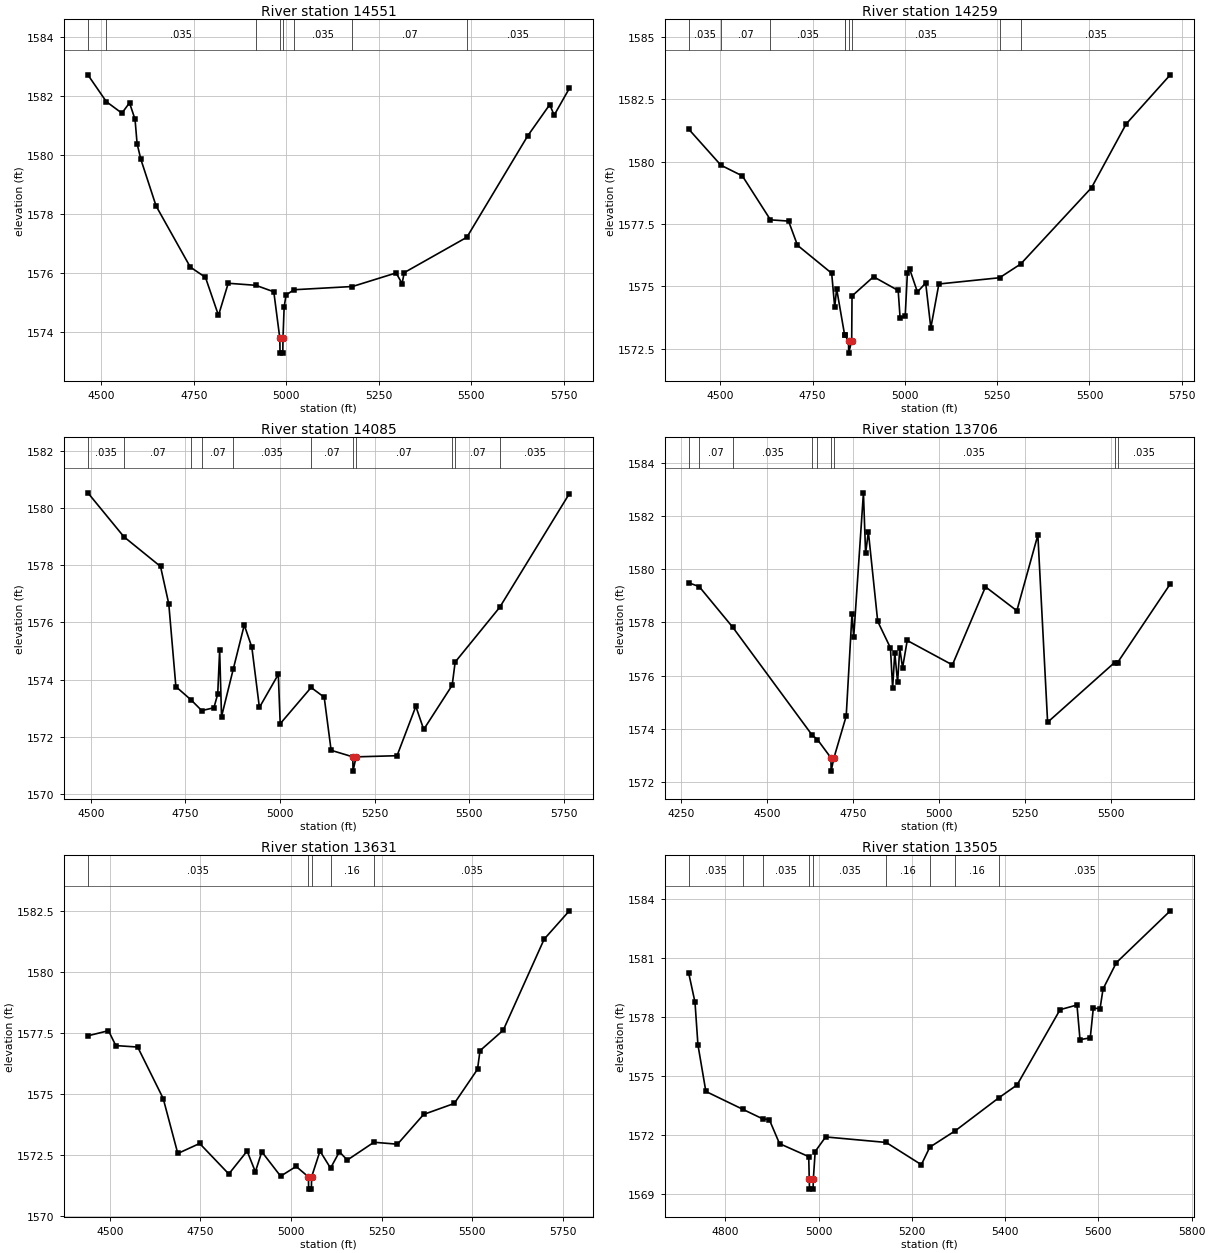
Type RM Length L Ch R = 1,14551,292,292,292
BEGIN DESCRIPTION:
Mapping XS a1b41520
END DESCRIPTION:
XS GIS Cut Line= 3
      1599548.20      6975587.65      1599428.41      6975061.62
      1599068.19      6974391.39
#Sta/Elev= 30
  4464.1 1582.73  4514.0 1581.82  4556.0 1581.43  4576.6 1581.78  4591.5 1581.22
  4597.1 1580.39  4607.3 1579.86  4648.4 1578.28  4740.7 1576.21  4781.7 1575.86
  4816.9 1574.57  4843.2 1575.66  4917.9 1575.59  4966.3 1575.37  4982.6 1573.79
  4983.1 1573.29  4990.6 1573.29  4991.1 1573.79  4994.2 1574.85  4999.3 1575.26
  5020.7 1575.44  5178.8 1575.55  5296.6 1576.01  5312.8 1575.65  5318.5 1576.02
  5487.7 1577.22  5652.1 1580.66  5711.6 1581.72  5723.5 1581.36  5764.5 1582.27
#Mann=8,-1,0
  4464.1   0.045       0  4514.0   0.035       0  4917.9    0.07       0
  4982.6    0.07       0  4991.1    0.07       0  5020.7   0.035       0
  5178.8    0.07       0  5487.7   0.035       0
Bank Sta=4982.6,4991.1
Exp/Cntr=0.3,0.1

Type RM Length L Ch R = 1,14259,174,174,174
BEGIN DESCRIPTION:
Mapping XS 17c2cdb2
END DESCRIPTION:
XS GIS Cut Line= 3
      1599744.38      6975414.02      1599605.50      6974844.61
      1599215.71      6974241.74
#Sta/Elev= 30
  4414.8 1581.30  4501.7 1579.86  4559.9 1579.43  4636.0 1577.67  4685.0 1577.62
  4709.2 1576.65  4801.8 1575.53  4810.0 1574.17  4815.2 1574.91  4836.8 1573.06
  4837.4 1573.04  4847.4 1572.83  4847.9 1572.33  4856.0 1572.83  4856.9 1574.62
  4915.1 1575.39  4981.9 1574.84  4987.1 1573.74  5000.9 1573.81  5006.9 1575.56
  5012.9 1575.70  5034.0 1574.78  5056.4 1575.14  5070.3 1573.34  5092.1 1575.10
  5256.5 1575.35  5313.7 1575.90  5505.6 1578.96  5599.3 1581.51  5718.8 1583.48
#Mann=9,-1,0
  4414.8   0.035       0  4501.7    0.07       0  4636.0   0.035       0
  4836.8    0.07       0  4837.4   0.035       0  4847.4   0.035       0
  4856.0   0.035       0  5256.5    0.07       0  5313.7   0.035       0
Bank Sta=4847.4,4856
Exp/Cntr=0.3,0.1

Type RM Length L Ch R = 1,14085,379,379,379
BEGIN DESCRIPTION:
Mapping XS 6653c433
END DESCRIPTION:
XS GIS Cut Line= 6
      1599811.38      6975345.15      1599763.19      6975136.79
      1599746.27      6974964.92      1599773.61      6974682.37
      1599726.74      6974567.78      1599338.72      6974288.74
#Sta/Elev= 30
  4492.2 1580.54  4587.5 1579.00  4684.3 1577.96  4706.1 1576.65  4724.9 1573.75
  4765.5 1573.28  4793.3 1572.91  4825.4 1573.01  4835.5 1573.49  4840.6 1575.02
  4845.6 1572.70  4876.5 1574.36  4905.7 1575.91  4925.7 1575.13  4945.7 1573.02
  4995.7 1574.18  5000.7 1572.45  5082.4 1573.72  5117.0 1573.38  5135.3 1571.52
  5192.7 1571.29  5193.2 1570.79  5201.3 1571.29  5309.6 1571.33  5359.3 1573.06
  5380.1 1572.25  5455.4 1573.80  5463.2 1574.61  5581.1 1576.53  5765.1 1580.51
#Mann=11,-1,0
  4492.2   0.035       0  4587.5    0.07       0  4765.5   0.035       0
  4793.3    0.07       0  4876.5   0.035       0  5082.4    0.07       0
  5192.7   0.035       0  5201.3    0.07       0  5455.4   0.035       0
  5463.2    0.07       0  5581.1   0.035       0
Bank Sta=5192.7,5201.3
Exp/Cntr=0.3,0.1

Type RM Length L Ch R = 1,13706,75,75,75
BEGIN DESCRIPTION:
Mapping XS 937d8be6
END DESCRIPTION:
XS GIS Cut Line= 6
      1599897.31      6975285.23      1599881.68      6974787.84
      1599970.22      6974588.62      1599912.93      6974501.38
      1599747.57      6974451.90      1599486.13      6974152.74
#Sta/Elev= 30
  4271.5 1579.49  4301.7 1579.35  4400.0 1577.81  4630.5 1573.76  4646.1 1573.59
  4685.5 1572.90  4686.0 1572.40  4694.2 1572.90  4729.9 1574.47  4746.7 1578.30
  4751.8 1577.45  4780.1 1582.88  4786.4 1580.60  4794.5 1581.41  4821.7 1578.04
  4858.8 1577.04  4865.1 1575.52  4871.4 1576.86  4879.6 1575.74  4885.9 1577.03
  4894.1 1576.29  4907.6 1577.32  5039.2 1576.40  5135.6 1579.34  5226.9 1578.44
  5288.1 1581.29  5316.5 1574.24  5511.6 1576.49  5520.4 1576.49  5673.7 1579.45
#Mann=9,-1,0
  4271.5   0.035       0  4301.7    0.07       0  4400.0   0.035       0
  4630.5    0.07       0  4646.1   0.035       0  4685.5   0.035       0
  4694.2   0.035       0  5511.6    0.07       0  5520.4   0.035       0
Bank Sta=4685.5,4694.2
Exp/Cntr=0.3,0.1

Type RM Length L Ch R = 1,13631,126,126,126
BEGIN DESCRIPTION:
Mapping XS e7d6a321
END DESCRIPTION:
XS GIS Cut Line= 6
      1600017.10      6975114.63      1600058.77      6974717.52
      1600035.33      6974558.67      1599975.43      6974446.69
      1599829.60      6974364.66      1599480.68      6974044.38
#Sta/Elev= 30
  4439.7 1577.40  4496.6 1577.61  4516.7 1577.00  4577.1 1576.94  4647.5 1574.83
  4687.7 1572.58  4748.0 1572.99  4828.4 1571.74  4878.9 1572.68  4901.6 1571.83
  4919.4 1572.65  4971.3 1571.65  5014.1 1572.05  5048.0 1571.62  5048.5 1571.12
  5056.2 1571.12  5056.7 1571.62  5079.9 1572.68  5109.0 1571.98  5133.4 1572.65
  5155.1 1572.31  5228.6 1573.04  5293.6 1572.96  5365.7 1574.18  5450.2 1574.63
  5514.3 1576.03  5521.1 1576.79  5585.2 1577.63  5698.1 1581.36  5767.5 1582.52
#Mann=5,-1,0
  4439.7   0.035       0  5048.0   0.035       0  5056.7   0.035       0
  5109.0    0.16       0  5228.6   0.035       0
Bank Sta=5048,5056.7
Exp/Cntr=0.3,0.1

Type RM Length L Ch R = 1,13505,443,443,443
BEGIN DESCRIPTION:
Mapping XS 33b08a1d
END DESCRIPTION:
XS GIS Cut Line= 3
      1600255.05      6974755.94      1600142.19      6974500.68
      1599652.60      6973927.77
#Sta/Elev= 30
  4721.4 1580.22  4734.7 1578.76  4741.0 1576.60  4758.0 1574.23  4836.6 1573.33
  4879.7 1572.84  4894.1 1572.80  4916.0 1571.58  4978.6 1570.92  4979.8 1569.77
  4980.3 1569.27  4988.0 1569.27  4988.5 1569.77  4992.5 1571.18  5014.9 1571.92
  5144.7 1571.64  5220.2 1570.51  5238.3 1571.40  5293.4 1572.24  5386.0 1573.90
  5425.5 1574.56  5517.7 1578.38  5554.0 1578.62  5560.5 1576.86  5582.5 1576.95
  5589.1 1578.47  5603.4 1578.42  5609.9 1579.43  5638.5 1580.77  5754.1 1583.40
#Mann=9,-1,0
  4721.4   0.035       0  4836.6    0.07       0  4879.7   0.035       0
  4979.8   0.035       0  4988.5   0.035       0  5144.7    0.16       0
  5238.3   0.035       0  5293.4    0.16       0  5386.0   0.035       0
Bank Sta=4979.8,4988.5
Exp/Cntr=0.3,0.1

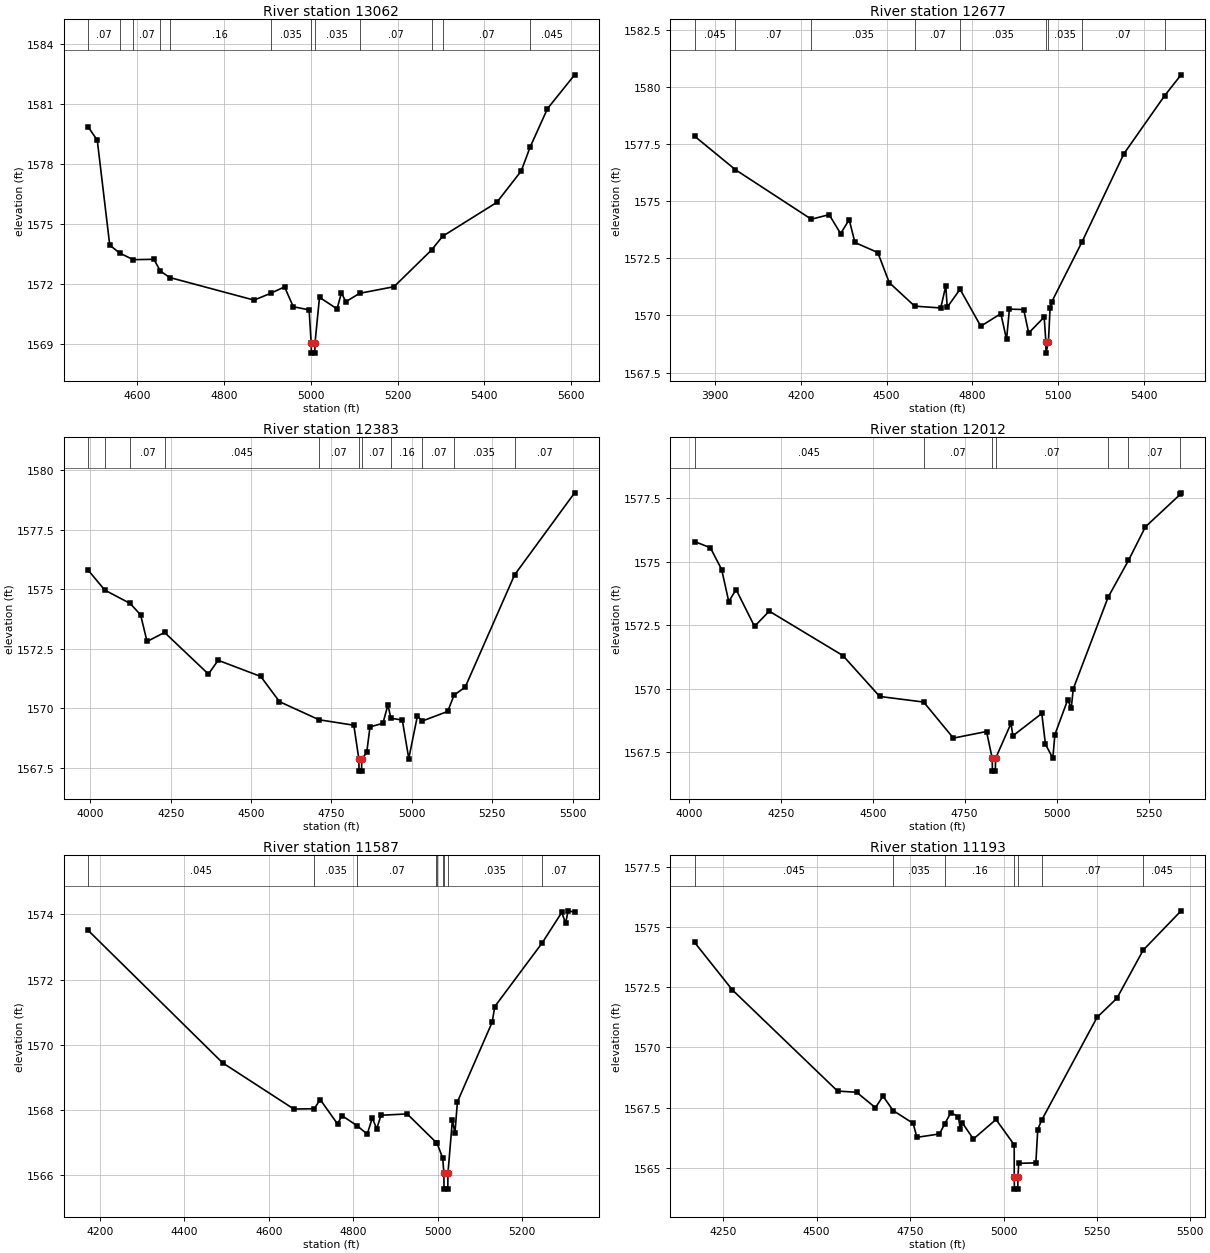
Type RM Length L Ch R = 1,13062,385,385,385
BEGIN DESCRIPTION:
Mapping XS 18cd9291
END DESCRIPTION:
XS GIS Cut Line= 3
      1600284.55      6974748.97      1600241.14      6974240.27
      1600154.34      6973636.13
#Sta/Elev= 30
  4487.1 1579.87  4508.2 1579.20  4536.9 1573.96  4559.8 1573.56  4591.3 1573.23
  4638.6 1573.25  4653.7 1572.66  4675.0 1572.34  4869.5 1571.21  4907.6 1571.55
  4939.7 1571.87  4959.8 1570.88  4996.3 1570.72  5001.0 1569.06  5001.5 1568.56
  5009.3 1568.56  5009.8 1569.06  5020.2 1571.35  5060.6 1570.77  5070.7 1571.57
  5080.9 1571.13  5112.7 1571.55  5191.9 1571.88  5278.6 1573.72  5303.8 1574.40
  5428.5 1576.09  5484.9 1577.66  5505.5 1578.86  5545.5 1580.78  5608.0 1582.47
#Mann=12,-1,0
  4487.1    0.07       0  4559.8    0.16       0  4591.3    0.07       0
  4653.7   0.035       0  4675.0    0.16       0  4907.6   0.035       0
  5001.0   0.035       0  5009.8   0.035       0  5112.7    0.07       0
  5278.6   0.035       0  5303.8    0.07       0  5505.5   0.045       0
Bank Sta=5001,5009.8
Exp/Cntr=0.3,0.1

Type RM Length L Ch R = 1,12677,294,294,294
BEGIN DESCRIPTION:
Mapping XS 9104452e
END DESCRIPTION:
XS GIS Cut Line= 3
      1600571.25      6975358.39      1600609.45      6974188.22
      1600477.49      6973674.29
#Sta/Elev= 30
  3828.6 1577.86  3971.5 1576.39  4236.9 1574.22  4299.2 1574.42  4339.3 1573.59
  4369.3 1574.20  4389.3 1573.20  4469.3 1572.76  4509.4 1571.44  4598.3 1570.41
  4689.5 1570.33  4707.1 1571.30  4712.1 1570.36  4757.0 1571.15  4829.5 1569.53
  4899.6 1570.08  4919.6 1568.95  4929.6 1570.28  4979.6 1570.26  4997.0 1569.23
  5051.2 1569.93  5057.1 1568.85  5057.6 1568.35  5066.0 1568.85  5071.9 1570.33
  5077.3 1570.59  5182.5 1573.20  5330.0 1577.09  5472.7 1579.64  5530.0 1580.55
#Mann=9,-1,0
  3828.6   0.045       0  3971.5    0.07       0  4236.9   0.035       0
  4598.3    0.07       0  4757.0   0.035       0  5057.1   0.035       0
  5066.0   0.035       0  5182.5    0.07       0  5472.7   0.045       0
Bank Sta=5057.1,5066
Exp/Cntr=0.3,0.1

Type RM Length L Ch R = 1,12383,371,371,371
BEGIN DESCRIPTION:
Mapping XS 85221d40
END DESCRIPTION:
XS GIS Cut Line= 3
      1600786.53      6975240.34      1600887.22      6974240.30
      1600956.66      6973736.87
#Sta/Elev= 30
  3993.0 1575.80  4044.9 1574.96  4123.7 1574.40  4156.2 1573.92  4176.3 1572.80
  4230.8 1573.18  4367.2 1571.43  4397.4 1572.01  4529.9 1571.33  4588.3 1570.27
  4711.1 1569.51  4819.5 1569.28  4835.2 1567.85  4835.7 1567.35  4843.6 1567.35
  4844.1 1567.85  4859.7 1568.14  4869.8 1569.21  4910.0 1569.36  4925.5 1570.13
  4934.9 1569.57  4970.3 1569.50  4990.4 1567.88  5017.0 1569.65  5033.1 1569.46
  5111.5 1569.86  5131.5 1570.55  5165.9 1570.88  5319.5 1575.60  5506.3 1579.05
#Mann=11,-1,0
  3993.0   0.035       0  4044.9   0.045       0  4123.7    0.07       0
  4230.8   0.045       0  4711.1    0.07       0  4835.2    0.07       0
  4844.1    0.07       0  4934.9    0.16       0  5033.1    0.07       0
  5131.5   0.035       0  5319.5    0.07       0
Bank Sta=4835.2,4844.1
Exp/Cntr=0.3,0.1

Type RM Length L Ch R = 1,12012,425,425,425
BEGIN DESCRIPTION:
Mapping XS 75c04791
END DESCRIPTION:
XS GIS Cut Line= 3
      1601176.50      6975120.76      1601225.98      6974141.56
      1601184.48      6973801.73
#Sta/Elev= 30
  4015.6 1575.80  4058.4 1575.56  4089.2 1574.70  4108.5 1573.44  4128.5 1573.91
  4178.6 1572.46  4218.6 1573.06  4418.9 1571.31  4519.0 1569.70  4638.5 1569.48
  4719.3 1568.06  4809.4 1568.32  4824.9 1567.26  4825.4 1566.76  4833.4 1566.76
  4833.9 1567.26  4876.0 1568.64  4881.0 1568.15  4959.6 1569.03  4969.6 1567.82
  4989.6 1567.27  4995.3 1568.20  5029.9 1569.56  5039.9 1569.26  5045.2 1570.00
  5140.0 1573.61  5195.4 1575.06  5241.4 1576.38  5336.1 1577.66  5338.4 1577.72
#Mann=7,-1,0
  4015.6   0.045       0  4638.5    0.07       0  4824.9    0.07       0
  4833.9    0.07       0  5140.0   0.035       0  5195.4    0.07       0
  5336.1   0.045       0
Bank Sta=4824.9,4833.9
Exp/Cntr=0.3,0.1

Type RM Length L Ch R = 1,11587,394,394,394
BEGIN DESCRIPTION:
Mapping XS f344139b
END DESCRIPTION:
XS GIS Cut Line= 3
      1601773.72      6974942.74      1601582.75      6974139.83
      1601410.52      6973862.10
#Sta/Elev= 30
  4172.1 1573.51  4490.6 1569.44  4659.3 1568.02  4707.5 1568.03  4721.8 1568.31
  4762.9 1567.56  4773.1 1567.82  4808.8 1567.51  4833.1 1567.25  4845.1 1567.75
  4855.4 1567.41  4865.7 1567.83  4927.7 1567.87  4996.7 1566.99  4997.8 1566.99
  5011.9 1566.51  5014.5 1566.06  5015.0 1565.56  5023.8 1565.56  5024.3 1566.06
  5034.8 1567.69  5040.7 1567.27  5046.6 1568.24  5129.0 1570.69  5135.2 1571.17
  5247.7 1573.13  5293.7 1574.06  5302.9 1573.73  5308.8 1574.11  5324.2 1574.07
#Mann=9,-1,0
  4172.1   0.045       0  4707.5   0.035       0  4808.8    0.07       0
  4996.7   0.035       0  4997.8    0.07       0  5011.9   0.035       0
  5014.5    0.07       0  5024.3   0.035       0  5247.7    0.07       0
Bank Sta=5014.5,5024.3
Exp/Cntr=0.3,0.1

Type RM Length L Ch R = 1,11193,233,233,233
BEGIN DESCRIPTION:
Mapping XS 14973c4e
END DESCRIPTION:
XS GIS Cut Line= 3
      1601977.72      6974858.14      1601875.72      6974037.83
      1601789.27      6973570.99
#Sta/Elev= 30
  4173.6 1574.36  4274.5 1572.39  4556.0 1568.19  4607.1 1568.14  4657.4 1567.50
  4677.6 1567.98  4704.7 1567.38  4758.2 1566.85  4768.3 1566.27  4828.7 1566.41
  4842.4 1566.82  4859.0 1567.29  4879.1 1567.13  4884.3 1566.62  4889.4 1566.88
  4919.4 1566.20  4979.9 1567.01  5028.6 1565.96  5028.7 1564.62  5029.2 1564.12
  5038.1 1564.12  5038.6 1564.62  5040.7 1565.19  5086.5 1565.21  5091.6 1566.59
  5101.6 1566.97  5250.3 1571.25  5303.2 1572.04  5373.7 1574.04  5475.0 1575.67
#Mann=7,-1,0
  4173.6   0.045       0  4704.7   0.035       0  4842.4    0.16       0
  5028.7    0.07       0  5038.6    0.16       0  5101.6    0.07       0
  5373.7   0.045       0
Bank Sta=5028.7,5038.6
Exp/Cntr=0.3,0.1

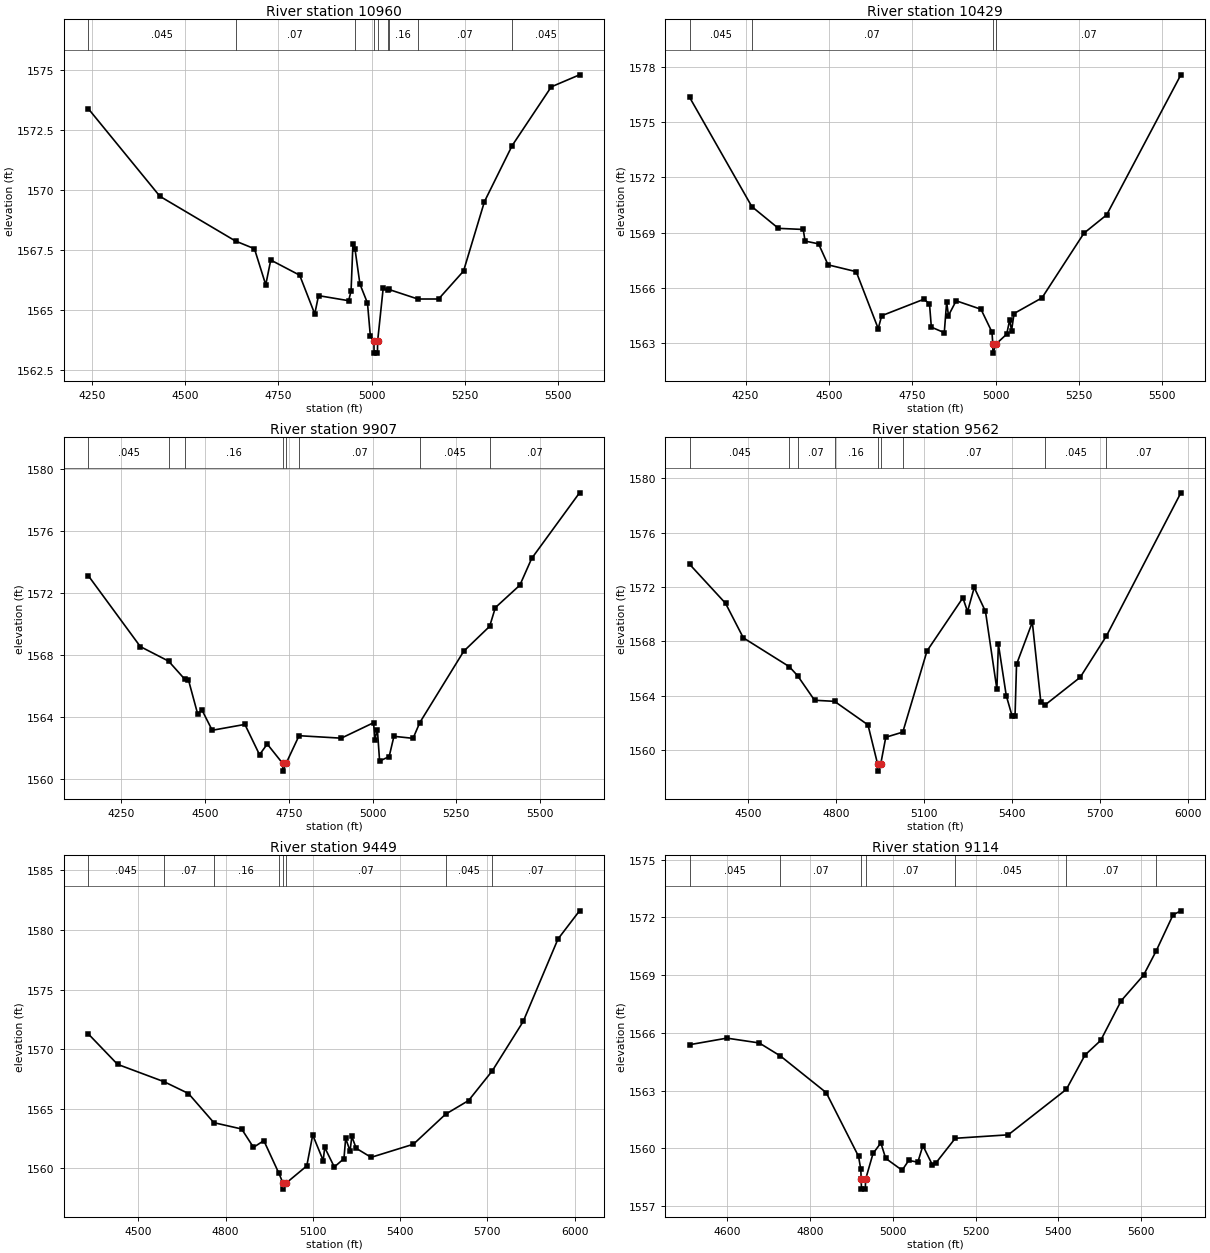
Type RM Length L Ch R = 1,10960,531,531,531
BEGIN DESCRIPTION:
Mapping XS c2ab9041
END DESCRIPTION:
XS GIS Cut Line= 3
      1602196.91      6974738.82      1602092.74      6973987.92
      1601903.99      6973462.91
#Sta/Elev= 30
  4240.9 1573.38  4432.6 1569.74  4635.2 1567.88  4685.9 1567.56  4716.2 1566.06
  4729.6 1567.09  4807.1 1566.46  4847.5 1564.85  4857.6 1565.61  4938.3 1565.40
  4944.8 1565.80  4949.8 1567.75  4955.3 1567.55  4968.6 1566.09  4988.8 1565.30
  4996.4 1563.94  5006.0 1563.72  5006.5 1563.22  5015.5 1563.22  5016.0 1563.72
  5030.8 1565.91  5042.6 1565.83  5045.6 1565.87  5123.7 1565.47  5179.3 1565.47
  5246.1 1566.63  5302.2 1569.52  5376.5 1571.85  5481.2 1574.29  5556.9 1574.79
#Mann=9,-1,0
  4240.9   0.045       0  4635.2    0.07       0  4955.3    0.16       0
  5006.0    0.07       0  5016.0    0.16       0  5042.6    0.07       0
  5045.6    0.16       0  5123.7    0.07       0  5376.5   0.045       0
Bank Sta=5006,5016
Exp/Cntr=0.3,0.1

Type RM Length L Ch R = 1,10429,522,522,522
BEGIN DESCRIPTION:
Mapping XS ede1c635
END DESCRIPTION:
XS GIS Cut Line= 3
      1602702.56      6974571.71      1602318.43      6973736.18
      1602084.05      6973234.86
#Sta/Elev= 30
  4082.3 1576.33  4268.7 1570.41  4348.4 1569.23  4422.8 1569.17  4428.3 1568.54
  4468.8 1568.39  4497.3 1567.25  4581.7 1566.88  4647.7 1563.79  4658.1 1564.49
  4784.0 1565.38  4801.4 1565.15  4807.0 1563.87  4845.8 1563.57  4852.9 1565.23
  4858.4 1564.50  4881.4 1565.30  4955.9 1564.84  4988.9 1563.60  4991.2 1562.96
  4991.7 1562.46  5001.4 1562.96  5033.0 1563.49  5042.0 1564.27  5047.5 1563.67
  5055.1 1564.61  5138.9 1565.46  5264.8 1568.97  5332.7 1569.96  5555.3 1577.56
#Mann=4,-1,0
  4082.3   0.045       0  4268.7    0.07       0  4991.2    0.07       0
  5001.4    0.07       0
Bank Sta=4991.2,5001.4
Exp/Cntr=0.3,0.1

Type RM Length L Ch R = 1,9907,345,345,345
BEGIN DESCRIPTION:
Mapping XS d615928e
END DESCRIPTION:
XS GIS Cut Line= 5
      1602890.62      6974339.58      1602736.53      6973640.77
      1602660.57      6973527.92      1602545.56      6973393.37
      1602173.77      6973162.08
#Sta/Elev= 30
  4151.3 1573.13  4306.5 1568.55  4390.9 1567.61  4438.8 1566.45  4449.9 1566.42
  4477.4 1564.22  4490.8 1564.44  4521.1 1563.14  4618.7 1563.52  4662.4 1561.56
  4685.4 1562.25  4731.5 1561.00  4732.0 1560.50  4741.7 1561.00  4780.4 1562.79
  4906.4 1562.63  5002.9 1563.63  5006.6 1562.54  5014.3 1563.18  5020.9 1561.15
  5049.4 1561.44  5063.7 1562.75  5120.8 1562.62  5141.0 1563.64  5272.1 1568.25
  5349.5 1569.86  5366.5 1571.07  5439.7 1572.52  5475.0 1574.25  5617.8 1578.49
#Mann=8,-1,0
  4151.3   0.045       0  4390.9    0.07       0  4438.8    0.16       0
  4731.5    0.07       0  4741.7    0.16       0  4780.4    0.07       0
  5141.0   0.045       0  5349.5    0.07       0
Bank Sta=4731.5,4741.7
Exp/Cntr=0.3,0.1

Type RM Length L Ch R = 1,9562,113,113,113
BEGIN DESCRIPTION:
Mapping XS 3e91d162
END DESCRIPTION:
XS GIS Cut Line= 6
      1603020.82      6974328.72      1602912.31      6973638.60
      1602894.95      6973425.92      1602860.23      6973352.14
      1602684.45      6973323.93      1602233.02      6973100.38
#Sta/Elev= 30
  4301.5 1573.67  4423.7 1570.81  4484.4 1568.27  4641.2 1566.15  4669.4 1565.49
  4727.4 1563.68  4795.5 1563.60  4909.6 1561.87  4942.7 1558.97  4943.2 1558.47
  4952.9 1558.97  4970.3 1560.96  5028.4 1561.34  5111.1 1567.31  5233.3 1571.21
  5249.2 1570.20  5272.0 1571.97  5310.4 1570.21  5349.3 1564.49  5354.4 1567.81
  5381.3 1564.02  5401.6 1562.49  5411.2 1562.51  5416.3 1566.32  5470.2 1569.42
  5499.0 1563.58  5514.0 1563.34  5633.6 1565.37  5723.0 1568.41  5976.8 1578.93
#Mann=9,-1,0
  4301.5   0.045       0  4641.2    0.16       0  4669.4    0.07       0
  4795.5    0.16       0  4942.7    0.07       0  4952.9    0.16       0
  5028.4    0.07       0  5514.0   0.045       0  5723.0    0.07       0
Bank Sta=4942.7,4952.9
Exp/Cntr=0.3,0.1

Type RM Length L Ch R = 1,9449,335,335,335
BEGIN DESCRIPTION:
Mapping XS af51e046
END DESCRIPTION:
XS GIS Cut Line= 6
      1603096.78      6974226.72      1602977.42      6973562.64
      1602942.69      6973397.71      1602864.57      6973278.35
      1602703.98      6973250.14      1602215.72      6973020.12
#Sta/Elev= 30
  4328.1 1571.27  4428.4 1568.72  4588.5 1567.26  4672.3 1566.27  4759.6 1563.82
  4855.1 1563.29  4895.8 1561.75  4931.5 1562.31  4983.2 1559.57  4997.4 1558.74
  4997.9 1558.24  5007.8 1558.74  5079.1 1560.19  5099.5 1562.79  5135.6 1560.64
  5140.7 1561.74  5173.8 1560.10  5206.9 1560.80  5212.8 1562.51  5227.9 1561.44
  5233.9 1562.66  5249.0 1561.67  5300.3 1560.91  5445.6 1562.01  5556.2 1564.53
  5635.4 1565.68  5716.8 1568.17  5823.2 1572.32  5942.7 1579.24  6016.8 1581.61
#Mann=8,-1,0
  4328.1   0.045       0  4588.5    0.07       0  4759.6    0.16       0
  4983.2    0.07       0  4997.4    0.07       0  5007.8    0.07       0
  5556.2   0.045       0  5716.8    0.07       0
Bank Sta=4997.4,5007.8
Exp/Cntr=0.3,0.1

Type RM Length L Ch R = 1,9114,365,365,365
BEGIN DESCRIPTION:
Mapping XS 49eed71c
END DESCRIPTION:
XS GIS Cut Line= 3
      1603332.61      6973748.14      1603150.30      6973290.22
      1602819.15      6972679.85
#Sta/Elev= 30
  4509.0 1565.39  4598.9 1565.73  4677.1 1565.48  4728.5 1564.80  4839.0 1562.90
  4917.2 1559.59  4922.6 1558.91  4923.7 1558.39  4924.2 1557.89  4933.6 1557.89
  4934.1 1558.39  4952.2 1559.74  4971.1 1560.29  4982.7 1559.49  5022.5 1558.87
  5038.5 1559.38  5060.5 1559.29  5072.7 1560.15  5095.4 1559.16  5104.2 1559.25
  5151.0 1560.53  5279.1 1560.71  5419.5 1563.07  5464.5 1564.85  5502.5 1565.61
  5552.0 1567.67  5606.2 1569.00  5636.7 1570.26  5677.4 1572.13  5696.3 1572.34
#Mann=7,-1,0
  4509.0   0.045       0  4728.5    0.07       0  4923.7    0.07       0
  4934.1    0.07       0  5151.0   0.045       0  5419.5    0.07       0
  5636.7   0.045       0
Bank Sta=4923.7,4934.1
Exp/Cntr=0.3,0.1

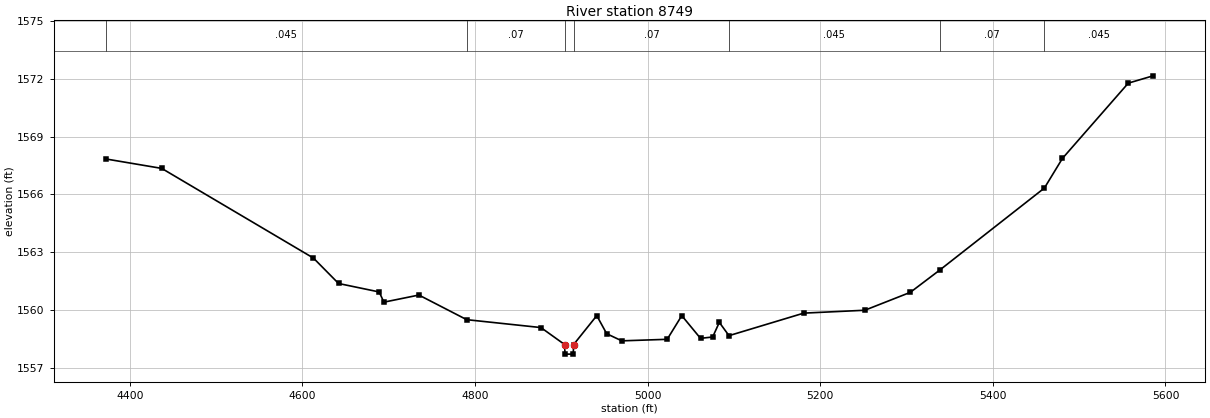
Type RM Length L Ch R = 1,8749,547,547,547
BEGIN DESCRIPTION:
Mapping XS 6d86edea
END DESCRIPTION:
XS GIS Cut Line= 3
      1603655.93      6973611.36      1603408.55      6973034.14
      1603179.25      6972495.51
#Sta/Elev= 30
  4372.2 1567.84  4436.9 1567.35  4612.7 1562.69  4641.8 1561.37  4688.9 1560.93
  4694.3 1560.40  4734.9 1560.77  4790.3 1559.49  4876.3 1559.08  4903.7 1558.20
  4904.2 1557.70  4913.7 1557.70  4914.2 1558.20  4941.0 1559.70  4952.5 1558.76
  4970.0 1558.39  5022.6 1558.47  5039.5 1559.70  5061.2 1558.52  5075.3 1558.59
  5083.0 1559.35  5094.2 1558.66  5180.8 1559.83  5251.6 1559.98  5304.3 1560.91
  5338.2 1562.06  5459.7 1566.33  5480.6 1567.87  5556.9 1571.78  5585.6 1572.16
#Mann=7,-1,0
  4372.2   0.045       0  4790.3    0.07       0  4903.7    0.07       0
  4914.2    0.07       0  5094.2   0.045       0  5338.2    0.07       0
  5459.7   0.045       0
Bank Sta=4903.7,4914.2
Exp/Cntr=0.3,0.1