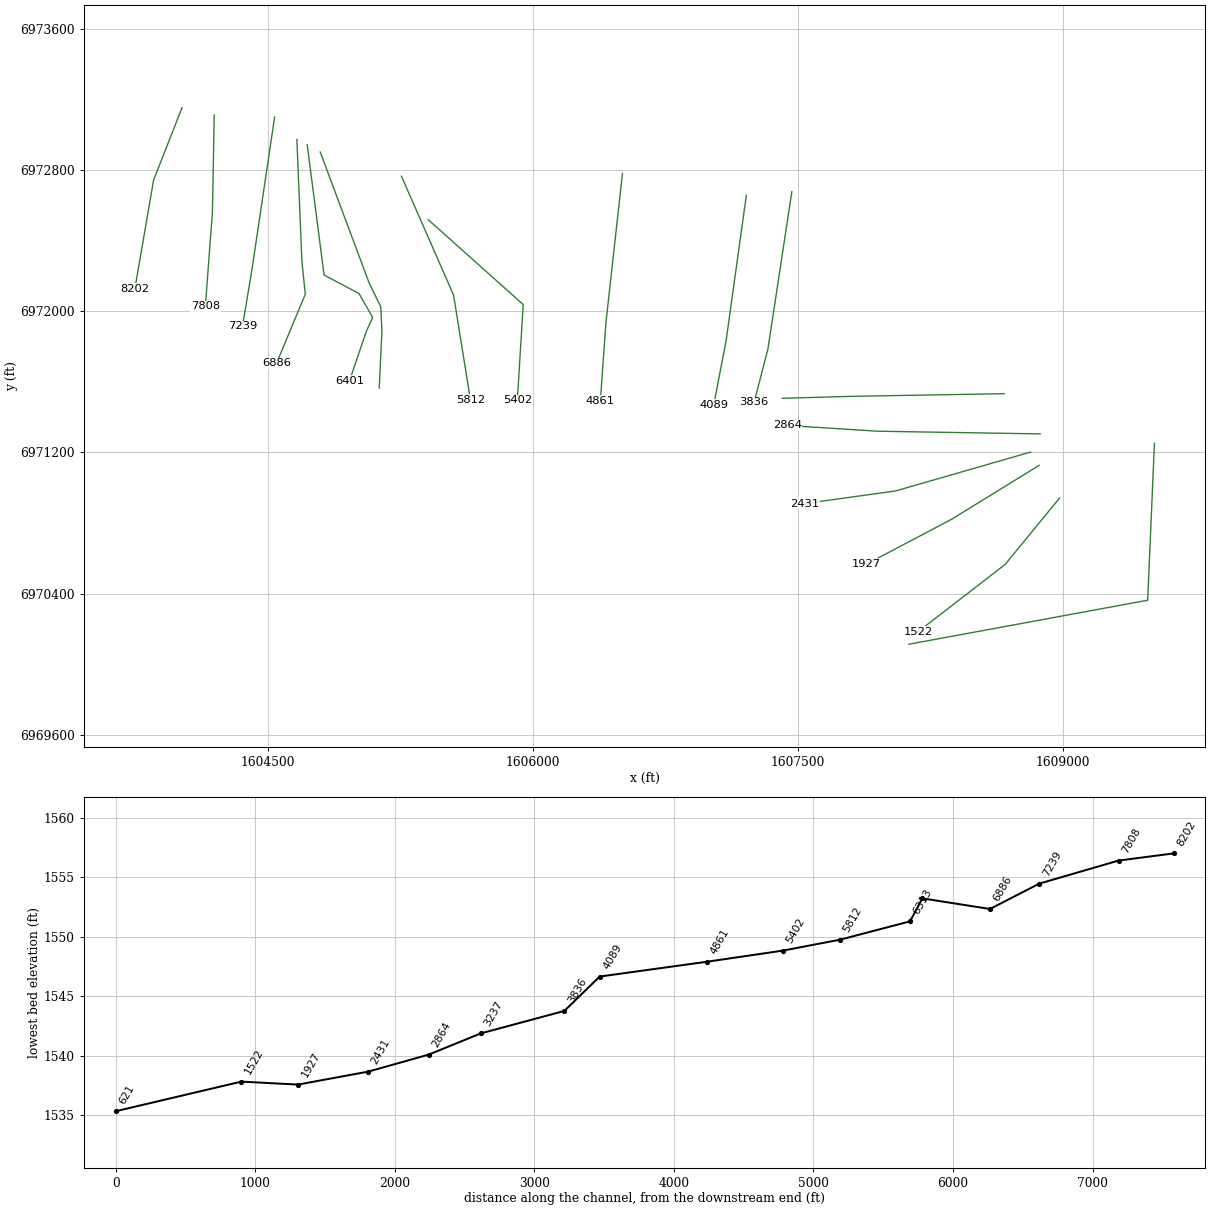
HEC-RAS study Chimney Creek 1121.prj: Chimney Creek 1121 Base Level Engineering

--- Chimney Creek 1121.g01 (geometry) --- (continued)

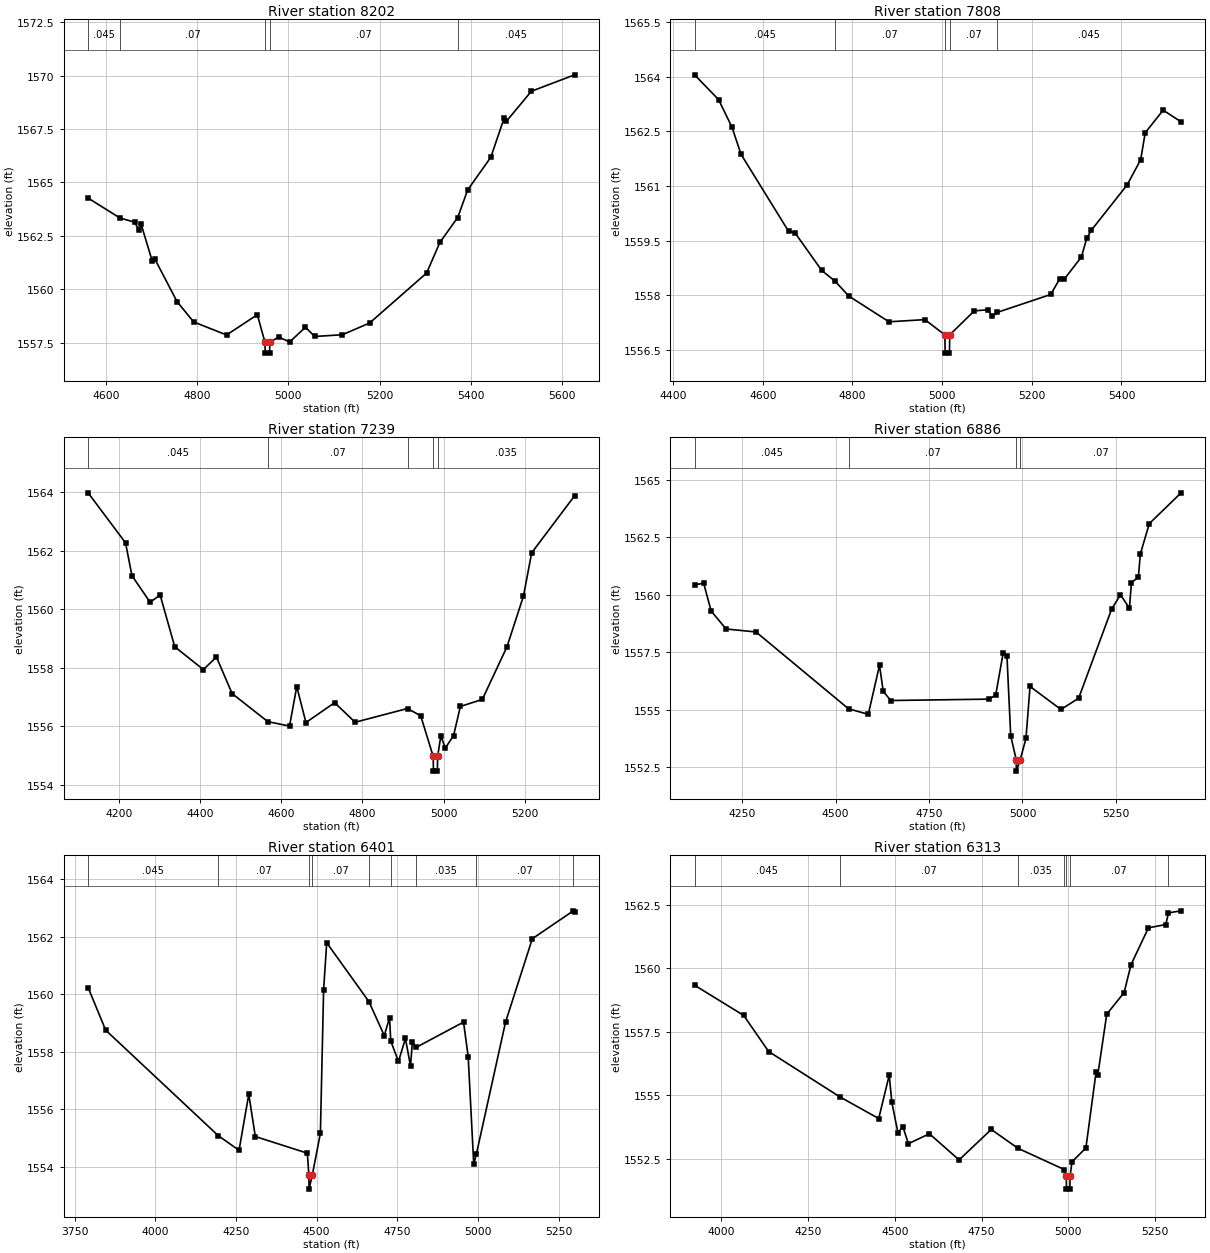
Type RM Length L Ch R = 1,8202,394,394,394
BEGIN DESCRIPTION:
Mapping XS 67712b35
END DESCRIPTION:
XS GIS Cut Line= 3
      1604011.69      6973153.09      1603850.25      6972741.66
      1603744.34      6972127.09
#Sta/Elev= 30
  4561.5 1564.27  4630.9 1563.34  4663.6 1563.14  4672.3 1562.77  4677.7 1563.04
  4702.1 1561.31  4707.5 1561.42  4756.4 1559.42  4792.6 1558.47  4864.8 1557.86
  4932.2 1558.81  4948.9 1557.51  4949.4 1557.01  4959.0 1557.01  4959.5 1557.51
  4978.7 1557.77  5002.7 1557.53  5037.6 1558.22  5057.9 1557.79  5118.2 1557.87
  5178.1 1558.42  5302.9 1560.76  5331.9 1562.19  5371.0 1563.36  5392.8 1564.65
  5443.5 1566.18  5472.5 1568.00  5477.5 1567.86  5532.3 1569.27  5627.1 1570.04
#Mann=5,-1,0
  4561.5   0.045       0  4630.9    0.07       0  4948.9    0.07       0
  4959.5    0.07       0  5371.0   0.045       0
Bank Sta=4948.9,4959.5
Exp/Cntr=0.3,0.1

Type RM Length L Ch R = 1,7808,569,569,569
BEGIN DESCRIPTION:
Mapping XS 8859818a
END DESCRIPTION:
XS GIS Cut Line= 3
      1604193.99      6973111.44      1604183.58      6972561.11
      1604143.65      6972028.14
#Sta/Elev= 30
  4448.0 1564.05  4501.5 1563.37  4531.5 1562.61  4551.5 1561.87  4657.8 1559.75
  4671.5 1559.72  4731.5 1558.68  4761.7 1558.38  4791.5 1557.98  4881.5 1557.27
  4961.5 1557.33  5006.2 1556.91  5006.7 1556.41  5016.4 1556.41  5016.9 1556.91
  5071.7 1557.57  5101.8 1557.60  5111.9 1557.42  5123.3 1557.53  5242.2 1558.02
  5262.3 1558.45  5272.3 1558.44  5310.7 1559.05  5322.4 1559.56  5332.5 1559.78
  5412.7 1561.03  5442.8 1561.72  5452.9 1562.46  5492.9 1563.08  5532.9 1562.76
#Mann=5,-1,0
  4448.0   0.045       0  4761.7    0.07       0  5006.2    0.07       0
  5016.9    0.07       0  5123.3   0.045       0
Bank Sta=5006.2,5016.9
Exp/Cntr=0.3,0.1

Type RM Length L Ch R = 1,7239,353,353,353
BEGIN DESCRIPTION:
Mapping XS dabea7a1
END DESCRIPTION:
XS GIS Cut Line= 3
      1604536.00      6973099.26      1604407.54      6972234.72
      1604353.72      6971913.53
#Sta/Elev= 30
  4123.4 1563.98  4215.7 1562.27  4231.5 1561.15  4276.3 1560.24  4301.0 1560.49
  4337.0 1558.72  4407.7 1557.94  4439.8 1558.37  4478.5 1557.12  4566.6 1556.16
  4620.1 1556.01  4637.9 1557.36  4660.5 1556.13  4731.3 1556.81  4781.8 1556.14
  4911.0 1556.61  4943.6 1556.36  4974.4 1554.97  4974.9 1554.47  4984.7 1554.47
  4985.2 1554.97  4993.2 1555.67  5004.2 1555.26  5024.5 1555.68  5041.4 1556.68
  5095.5 1556.92  5156.3 1558.72  5196.9 1560.45  5217.2 1561.93  5323.1 1563.88
#Mann=5,-1,0
  4123.4   0.045       0  4566.6    0.07       0  4911.0   0.035       0
  4974.4   0.035       0  4985.2   0.035       0
Bank Sta=4974.4,4985.2
Exp/Cntr=0.3,0.1

Type RM Length L Ch R = 1,6886,485,485,485
BEGIN DESCRIPTION:
Mapping XS 832a10c9
END DESCRIPTION:
XS GIS Cut Line= 4
      1604662.04      6972972.31      1604690.25      6972284.34
      1604709.78      6972095.54      1604547.03      6971704.94
#Sta/Elev= 30
  4122.8 1560.44  4147.1 1560.51  4167.1 1559.30  4207.2 1558.52  4287.2 1558.39
  4534.6 1555.05  4587.5 1554.81  4617.5 1556.94  4627.5 1555.81  4647.5 1555.41
  4909.7 1555.47  4928.3 1555.64  4948.4 1557.49  4958.5 1557.33  4968.5 1553.88
  4983.2 1552.84  4983.7 1552.34  4994.0 1552.84  5009.3 1553.76  5020.2 1556.02
  5103.0 1555.02  5150.2 1555.51  5238.4 1559.38  5262.2 1560.01  5286.1 1559.42
  5291.5 1560.54  5309.9 1560.77  5315.3 1561.78  5339.2 1563.10  5424.3 1564.44
#Mann=4,-1,0
  4122.8   0.045       0  4534.6    0.07       0  4983.2    0.07       0
  4994.0    0.07       0
Bank Sta=4983.2,4994
Exp/Cntr=0.3,0.1

Type RM Length L Ch R = 1,6401,88,88,88
BEGIN DESCRIPTION:
Mapping XS 5aaf6cfd
END DESCRIPTION:
XS GIS Cut Line= 6
      1604720.63      6972941.90      1604816.12      6972204.05
      1605013.60      6972099.88      1605091.72      6971963.16
      1605057.00      6971889.38      1604959.68      6971603.90
#Sta/Elev= 30
  3791.7 1560.24  3846.1 1558.76  4195.0 1555.09  4259.5 1554.58  4289.7 1556.53
  4309.9 1555.06  4471.2 1554.48  4475.9 1553.73  4476.4 1553.23  4486.7 1553.73
  4511.6 1555.17  4521.6 1560.16  4531.2 1561.80  4662.2 1559.75  4709.6 1558.57
  4725.9 1559.19  4729.8 1558.38  4753.6 1557.67  4775.2 1558.47  4791.0 1557.51
  4796.7 1558.35  4808.4 1558.16  4955.3 1559.04  4969.7 1557.84  4986.9 1554.10
  4994.9 1554.44  5085.5 1559.04  5168.5 1561.94  5295.6 1562.91  5299.6 1562.88
#Mann=9,-1,0
  3791.7   0.045       0  4195.0    0.07       0  4475.9    0.07       0
  4486.7    0.07       0  4662.2   0.035       0  4729.8    0.07       0
  4808.4   0.035       0  4994.9    0.07       0  5295.6   0.035       0
Bank Sta=4475.9,4486.7
Exp/Cntr=0.3,0.1

Type RM Length L Ch R = 1,6313,501,501,501
BEGIN DESCRIPTION:
Mapping XS 5c80f150
END DESCRIPTION:
XS GIS Cut Line= 5
      1604794.41      6972900.66      1605070.02      6972162.81
      1605137.30      6972023.93      1605143.81      6971885.04
      1605128.62      6971563.91
#Sta/Elev= 30
  3922.8 1559.33  4064.4 1558.14  4136.3 1556.72  4342.0 1554.93  4453.6 1554.08
  4483.9 1555.79  4491.4 1554.72  4508.9 1553.53  4523.4 1553.75  4539.2 1553.09
  4599.8 1553.48  4685.3 1552.45  4778.1 1553.65  4854.8 1552.91  4988.8 1552.07
  4994.4 1551.80  4994.9 1551.30  5004.7 1551.30  5005.2 1551.80  5010.9 1552.38
  5050.9 1552.92  5080.2 1555.91  5085.2 1555.80  5111.0 1558.19  5161.0 1559.04
  5181.0 1560.14  5231.1 1561.59  5281.2 1561.72  5289.0 1562.18  5325.3 1562.26
#Mann=7,-1,0
  3922.8   0.045       0  4342.0    0.07       0  4854.8   0.035       0
  4988.8    0.07       0  4994.4    0.07       0  5005.2    0.07       0
  5289.0   0.035       0
Bank Sta=4994.4,5005.2
Exp/Cntr=0.3,0.1

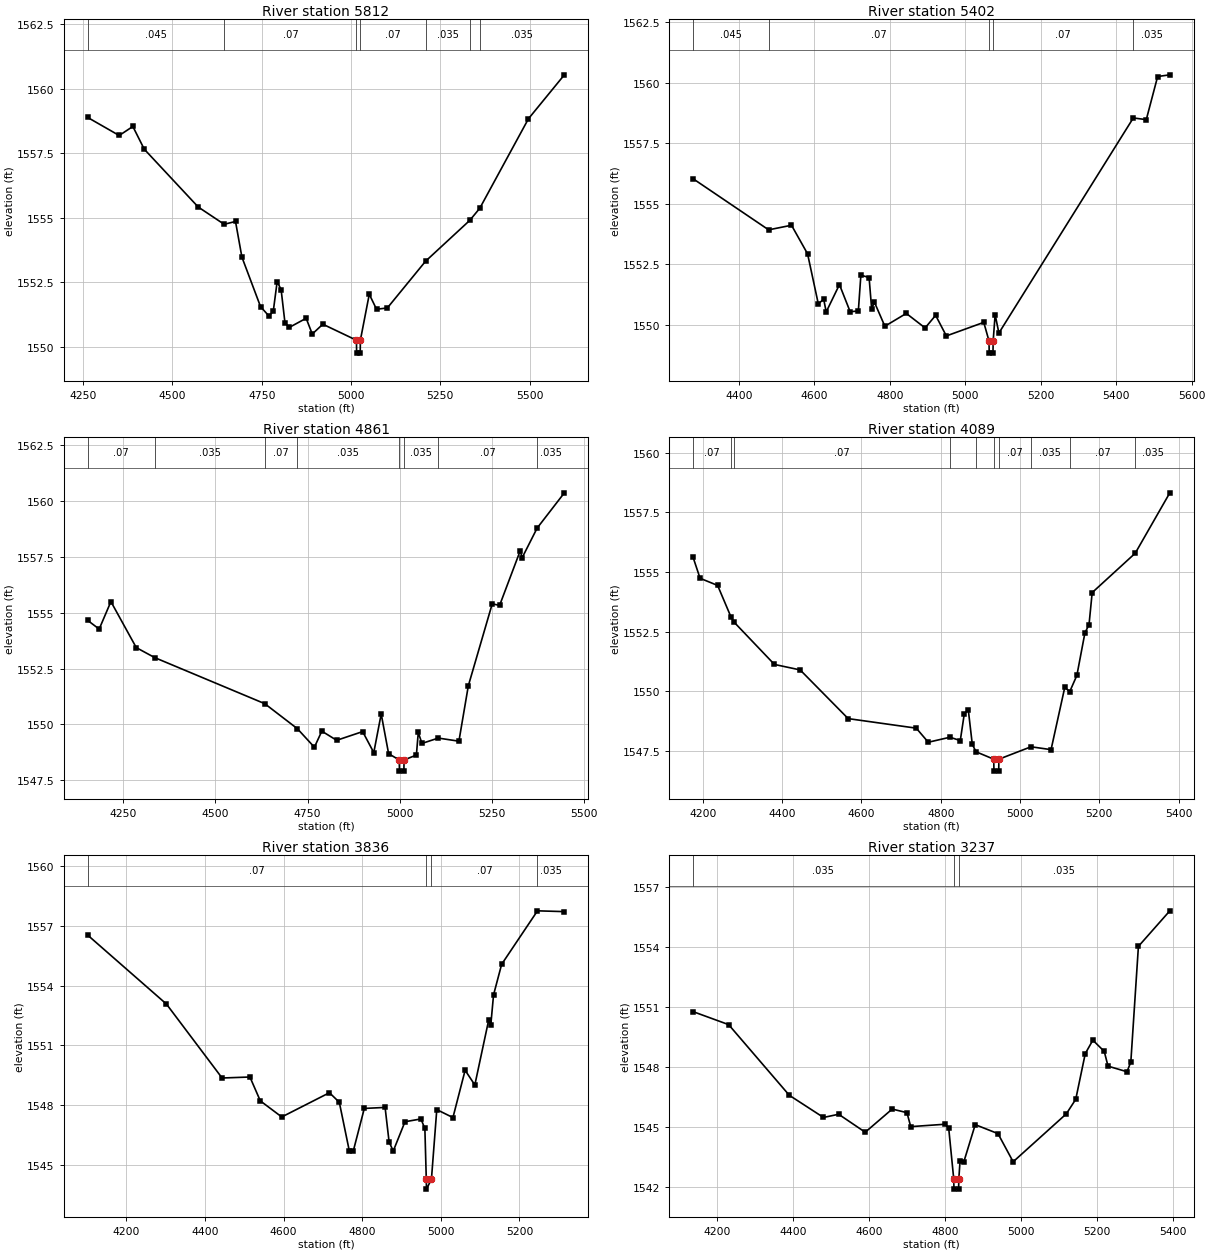
Type RM Length L Ch R = 1,5812,410,410,410
BEGIN DESCRIPTION:
Mapping XS b131654f
END DESCRIPTION:
XS GIS Cut Line= 3
      1605254.49      6972763.92      1605549.62      6972091.20
      1605645.11      6971498.76
#Sta/Elev= 30
  4262.5 1558.89  4350.9 1558.19  4389.1 1558.54  4421.0 1557.66  4572.1 1555.42
  4644.8 1554.75  4676.5 1554.86  4694.4 1553.48  4746.6 1551.56  4769.9 1551.20
  4782.2 1551.38  4793.1 1552.53  4804.2 1552.22  4815.0 1550.93  4827.6 1550.76
  4874.3 1551.11  4891.4 1550.50  4921.0 1550.88  5015.1 1550.26  5015.6 1549.76
  5025.6 1549.76  5026.1 1550.26  5051.0 1552.04  5071.3 1551.46  5101.6 1551.51
  5208.6 1553.32  5332.2 1554.90  5360.3 1555.37  5496.7 1558.84  5597.2 1560.54
#Mann=7,-1,0
  4262.5   0.045       0  4644.8    0.07       0  5015.1    0.07       0
  5026.1    0.07       0  5208.6   0.035       0  5332.2    0.07       0
  5360.3   0.035       0
Bank Sta=5015.1,5026.1
Exp/Cntr=0.3,0.1

Type RM Length L Ch R = 1,5402,541,541,541
BEGIN DESCRIPTION:
Mapping XS 01fe1895
END DESCRIPTION:
XS GIS Cut Line= 3
      1605406.24      6972517.56      1605944.50      6972036.80
      1605910.95      6971495.74
#Sta/Elev= 30
  4278.3 1556.04  4478.6 1553.93  4539.2 1554.12  4581.8 1552.94  4610.3 1550.87
  4624.5 1551.07  4631.2 1550.54  4666.3 1551.67  4694.7 1550.55  4716.4 1550.58
  4723.1 1552.06  4744.9 1551.96  4751.6 1550.68  4759.1 1550.94  4786.7 1549.95
  4843.5 1550.48  4893.4 1549.88  4921.3 1550.40  4949.7 1549.55  5048.9 1550.11
  5062.8 1549.34  5063.3 1548.84  5073.3 1548.84  5073.8 1549.34  5079.0 1550.43
  5089.0 1549.67  5445.3 1558.55  5479.7 1558.48  5509.8 1560.26  5542.1 1560.33
#Mann=5,-1,0
  4278.3   0.045       0  4478.6    0.07       0  5062.8    0.07       0
  5073.8    0.07       0  5445.3   0.035       0
Bank Sta=5062.8,5073.8
Exp/Cntr=0.3,0.1

Type RM Length L Ch R = 1,4861,772,772,772
BEGIN DESCRIPTION:
Mapping XS 0cf2c612
END DESCRIPTION:
XS GIS Cut Line= 3
      1606506.57      6972779.06      1606412.82      6971932.72
      1606381.58      6971492.85
#Sta/Elev= 30
  4153.8 1554.66  4185.1 1554.27  4216.9 1555.50  4285.7 1553.44  4336.0 1552.99
  4634.0 1550.93  4722.4 1549.81  4768.6 1548.98  4788.7 1549.70  4829.0 1549.29
  4899.4 1549.68  4929.6 1548.74  4949.7 1550.47  4969.8 1548.69  4998.7 1548.41
  4999.2 1547.91  5011.2 1547.91  5011.7 1548.41  5045.1 1548.63  5050.2 1549.64
  5060.2 1549.15  5104.5 1549.39  5160.4 1549.25  5185.9 1551.73  5250.7 1555.40
  5270.7 1555.33  5326.7 1557.78  5331.7 1557.46  5372.4 1558.79  5446.3 1560.37
#Mann=8,-1,0
  4153.8    0.07       0  4336.0   0.035       0  4634.0    0.07       0
  4722.4   0.035       0  4998.7   0.035       0  5011.7   0.035       0
  5104.5    0.07       0  5372.4   0.035       0
Bank Sta=4998.7,5011.7
Exp/Cntr=0.3,0.1

Type RM Length L Ch R = 1,4089,253,253,253
BEGIN DESCRIPTION:
Mapping XS 1eeda6f5
END DESCRIPTION:
XS GIS Cut Line= 3
      1607208.39      6972655.39      1607093.81      6971832.46
      1607023.49      6971467.84
#Sta/Elev= 30
  4175.5 1555.62  4193.1 1554.74  4237.4 1554.44  4270.8 1553.13  4278.4 1552.91
  4380.6 1551.13  4445.5 1550.90  4566.6 1548.86  4738.3 1548.46  4768.6 1547.87
  4823.3 1548.08  4849.3 1547.94  4859.4 1549.06  4869.5 1549.23  4879.6 1547.78
  4889.1 1547.47  4933.7 1547.16  4934.2 1546.66  4946.2 1546.66  4946.7 1547.16
  5027.7 1547.68  5078.2 1547.56  5112.8 1550.17  5125.3 1549.99  5143.3 1550.67
  5163.7 1552.46  5173.9 1552.79  5181.9 1554.14  5290.5 1555.79  5377.7 1558.32
#Mann=10,-1,0
  4175.5    0.07       0  4270.8   0.035       0  4278.4    0.07       0
  4823.3   0.035       0  4889.1    0.07       0  4933.7    0.07       0
  4946.7    0.07       0  5027.7   0.035       0  5125.3    0.07       0
  5290.5   0.035       0
Bank Sta=4933.7,4946.7
Exp/Cntr=0.3,0.1

Type RM Length L Ch R = 1,3836,599,599,599
BEGIN DESCRIPTION:
Mapping XS a359d7fb
END DESCRIPTION:
XS GIS Cut Line= 3
      1607466.21      6972676.25      1607330.79      6971785.59
      1607252.67      6971483.52
#Sta/Elev= 30
  4101.5 1556.55  4302.0 1553.08  4443.6 1549.36  4514.4 1549.41  4540.8 1548.21
  4595.4 1547.40  4716.7 1548.62  4741.8 1548.14  4767.3 1545.69  4777.4 1545.69
  4805.4 1547.83  4858.3 1547.88  4868.5 1546.14  4879.1 1545.69  4908.9 1547.16
  4949.4 1547.30  4959.5 1546.82  4963.1 1544.27  4963.6 1543.77  4976.2 1544.27
  4989.8 1547.77  5030.9 1547.37  5061.9 1549.75  5086.6 1549.01  5122.0 1552.29
  5127.2 1552.03  5134.2 1553.54  5154.8 1555.08  5246.0 1557.77  5314.4 1557.73
#Mann=4,-1,0
  4101.5    0.07       0  4963.1    0.07       0  4976.2    0.07       0
  5246.0   0.035       0
Bank Sta=4963.1,4976.2
Exp/Cntr=0.3,0.1

Type RM Length L Ch R = 1,3237,373,373,373
BEGIN DESCRIPTION:
Mapping XS 12dab302
END DESCRIPTION:
XS GIS Cut Line= 3
      1608668.71      6971532.12      1607800.62      6971516.92
      1607412.19      6971506.07
#Sta/Elev= 30
  4135.8 1550.77  4229.5 1550.12  4389.5 1546.58  4479.6 1545.47  4519.6 1545.63
  4589.6 1544.73  4660.7 1545.89  4699.6 1545.71  4709.6 1545.01  4799.6 1545.13
  4809.6 1544.95  4823.0 1542.38  4823.5 1541.88  4835.8 1541.88  4836.3 1542.38
  4839.6 1543.29  4849.6 1543.25  4879.6 1545.11  4939.6 1544.66  4979.6 1543.25
  5119.7 1545.65  5144.6 1546.38  5169.7 1548.67  5189.7 1549.34  5219.7 1548.78
  5229.7 1548.04  5279.7 1547.76  5289.8 1548.25  5309.8 1554.04  5392.6 1555.82
#Mann=3,-1,0
  4135.8   0.035       0  4823.0   0.035       0  4836.3   0.035       0
Bank Sta=4823,4836.3
Exp/Cntr=0.3,0.1

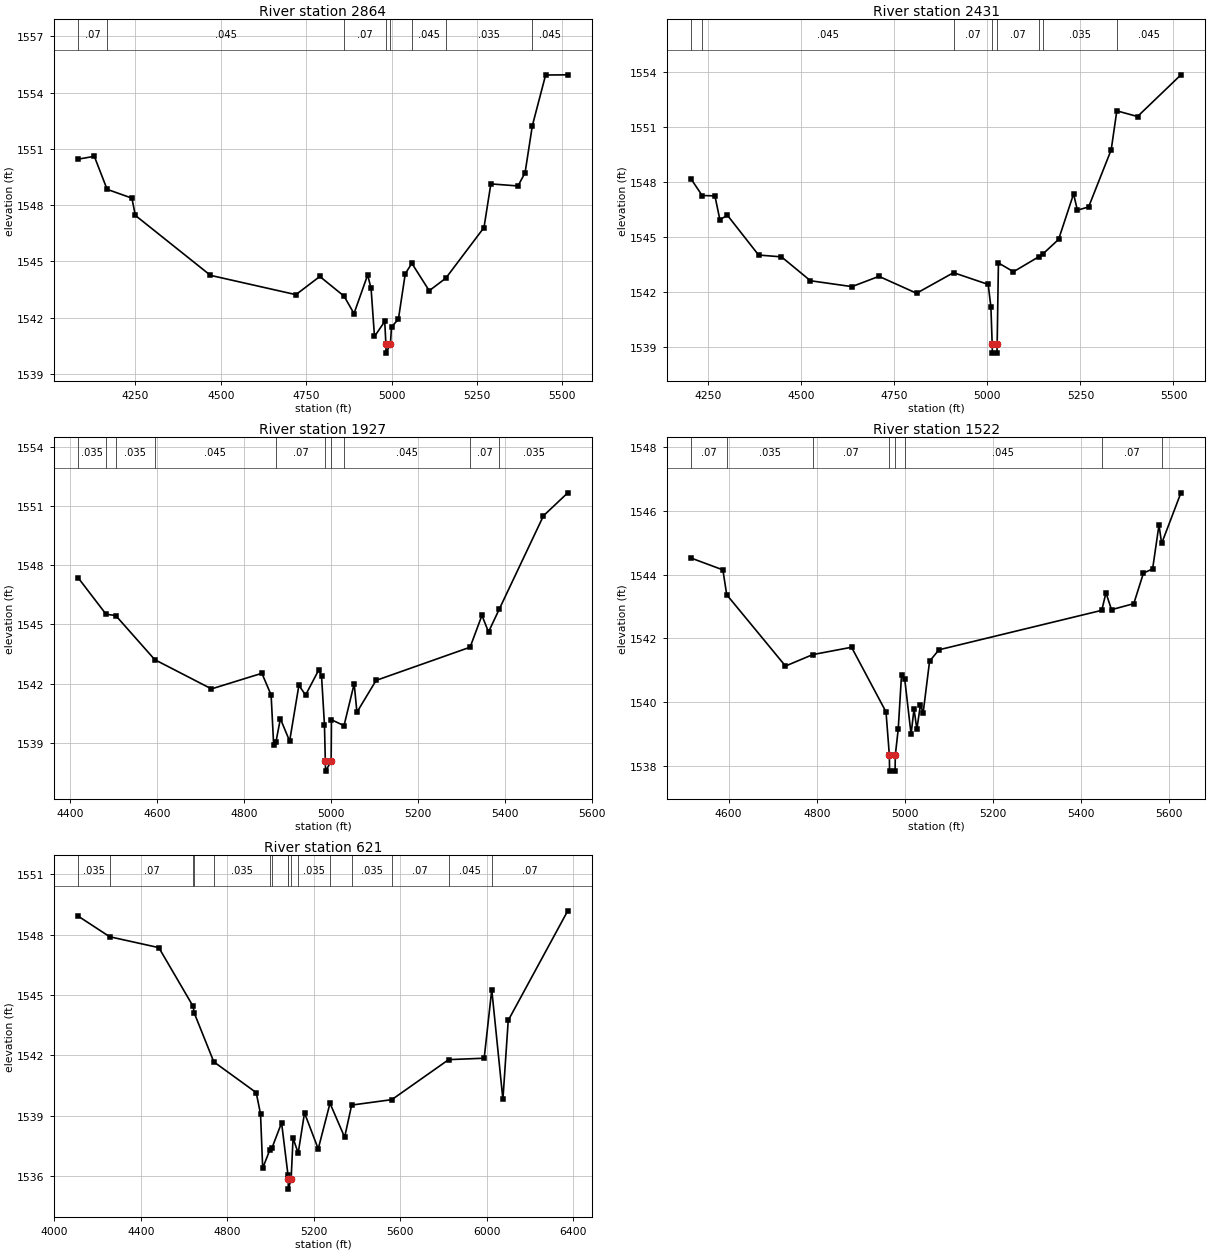
Type RM Length L Ch R = 1,2864,433,433,433
BEGIN DESCRIPTION:
Mapping XS c45fcaa6
END DESCRIPTION:
XS GIS Cut Line= 3
      1608872.68      6971304.25      1607950.36      6971319.44
      1607440.34      6971352.00
#Sta/Elev= 30
  4082.4 1550.45  4130.1 1550.60  4167.5 1548.84  4240.1 1548.37  4250.1 1547.45
  4470.1 1544.25  4720.2 1543.22  4790.2 1544.19  4861.2 1543.14  4890.2 1542.21
  4930.2 1544.27  4940.2 1543.55  4950.2 1540.99  4980.2 1541.79  4983.5 1540.60
  4984.0 1540.10  4996.9 1540.60  5000.0 1541.50  5020.2 1541.91  5040.3 1544.34
  5059.6 1544.89  5110.4 1543.43  5159.0 1544.10  5270.7 1546.80  5290.8 1549.13
  5370.3 1549.02  5391.0 1549.73  5412.2 1552.23  5451.1 1554.94  5515.9 1554.95
#Mann=8,-1,0
  4082.4    0.07       0  4167.5   0.045       0  4861.2    0.07       0
  4983.5    0.07       0  4996.9    0.07       0  5059.6   0.045       0
  5159.0   0.035       0  5412.2   0.045       0
Bank Sta=4983.5,4996.9
Exp/Cntr=0.3,0.1

Type RM Length L Ch R = 1,2431,504,504,504
BEGIN DESCRIPTION:
Mapping XS 109b0ece
END DESCRIPTION:
XS GIS Cut Line= 3
      1608818.90      6971201.29      1608054.61      6970981.25
      1607539.49      6970909.70
#Sta/Elev= 30
  4204.6 1548.14  4233.9 1547.25  4268.3 1547.23  4281.5 1545.94  4302.0 1546.17
  4385.6 1544.01  4447.1 1543.91  4524.9 1542.61  4636.3 1542.29  4708.9 1542.85
  4809.9 1541.93  4909.2 1543.05  5002.3 1542.41  5009.6 1541.18  5013.0 1539.17
  5013.5 1538.67  5025.9 1538.67  5026.4 1539.17  5029.8 1543.58  5070.2 1543.10
  5137.7 1543.91  5148.2 1544.05  5191.4 1544.86  5231.7 1547.34  5241.8 1546.45
  5272.1 1546.63  5332.7 1549.74  5347.8 1551.86  5403.4 1551.55  5520.0 1553.82
#Mann=8,-1,0
  4204.6   0.035       0  4233.9   0.045       0  4909.2    0.07       0
  5013.0    0.07       0  5026.4    0.07       0  5137.7   0.045       0
  5148.2   0.035       0  5347.8   0.045       0
Bank Sta=5013,5026.4
Exp/Cntr=0.3,0.1

Type RM Length L Ch R = 1,1927,405,405,405
BEGIN DESCRIPTION:
Mapping XS d29a2c5d
END DESCRIPTION:
XS GIS Cut Line= 3
      1608867.77      6971126.19      1608371.28      6970820.66
      1607890.36      6970567.17
#Sta/Elev= 30
  4417.8 1547.37  4482.2 1545.52  4504.6 1545.45  4594.3 1543.22  4724.8 1541.74
  4840.8 1542.53  4862.0 1541.43  4867.9 1538.88  4872.9 1539.03  4883.3 1540.23
  4904.6 1539.10  4925.9 1541.92  4941.3 1541.43  4972.1 1542.72  4978.0 1542.39
  4984.7 1539.93  4986.7 1538.08  4987.2 1537.58  5000.1 1538.08  5000.8 1540.18
  5029.7 1539.88  5053.1 1542.00  5059.4 1540.56  5103.5 1542.17  5319.8 1543.85
  5347.0 1545.46  5362.1 1544.62  5387.2 1545.79  5488.6 1550.50  5544.4 1551.66
#Mann=10,-1,0
  4417.8   0.035       0  4482.2    0.07       0  4504.6   0.035       0
  4594.3   0.045       0  4872.9    0.07       0  4986.7    0.07       0
  5000.1    0.07       0  5029.7   0.045       0  5319.8    0.07       0
  5387.2   0.035       0
Bank Sta=4986.7,5000.1
Exp/Cntr=0.3,0.1

Type RM Length L Ch R = 1,1522,901,901,901
BEGIN DESCRIPTION:
Mapping XS 838ce27a
END DESCRIPTION:
XS GIS Cut Line= 3
      1608983.43      6970941.31      1608674.41      6970564.58
      1608180.30      6970182.77
#Sta/Elev= 30
  4515.0 1544.52  4586.9 1544.15  4595.6 1543.37  4729.0 1541.13  4791.0 1541.49
  4879.0 1541.72  4957.2 1539.69  4964.8 1538.33  4965.3 1537.83  4977.8 1537.83
  4978.3 1538.33  4984.9 1539.14  4992.4 1540.84  4999.8 1540.71  5014.1 1538.99
  5020.8 1539.78  5027.2 1539.15  5035.3 1539.90  5041.6 1539.67  5056.1 1541.28
  5077.3 1541.64  5447.0 1542.88  5456.5 1543.43  5469.1 1542.90  5519.7 1543.09
  5541.6 1544.05  5562.4 1544.18  5576.9 1545.56  5582.9 1544.98  5626.7 1546.57
#Mann=8,-1,0
  4515.0    0.07       0  4595.6   0.035       0  4791.0    0.07       0
  4964.8   0.045       0  4978.3    0.07       0  4999.8   0.045       0
  5447.0    0.07       0  5582.9   0.035       0
Bank Sta=4964.8,4978.3
Exp/Cntr=0.3,0.1

Type RM Length L Ch R = 1,621,0,0,0
BEGIN DESCRIPTION:
Mapping XS 7feafe71
END DESCRIPTION:
XS GIS Cut Line= 3
      1609520.49      6971251.34      1609482.19      6970361.97
      1608130.02      6970113.00
#Sta/Elev= 30
  4109.8 1548.92  4256.5 1547.89  4483.5 1547.35  4642.1 1544.43  4647.3 1544.10
  4737.8 1541.67  4933.9 1540.14  4953.9 1539.08  4963.9 1536.38  4997.3 1537.30
  5007.7 1537.41  5051.3 1538.64  5081.2 1536.02  5081.9 1535.84  5082.4 1535.34
  5095.5 1535.84  5104.3 1537.88  5128.1 1537.13  5157.4 1539.13  5220.8 1537.34
  5275.3 1539.61  5342.9 1537.92  5375.4 1539.52  5561.3 1539.79  5824.1 1541.78
  5988.4 1541.85  6023.4 1545.26  6075.0 1539.80  6099.6 1543.73  6374.9 1549.18
#Mann=16,-1,0
  4109.8   0.035       0  4256.5    0.07       0  4642.1   0.035       0
  4647.3    0.07       0  4737.8   0.035       0  4997.3    0.07       0
  5007.7   0.035       0  5081.2    0.07       0  5081.9    0.07       0
  5095.5    0.07       0  5128.1   0.035       0  5275.3    0.07       0
  5375.4   0.035       0  5561.3    0.07       0  5824.1   0.045       0
  6023.4    0.07       0
Bank Sta=5081.9,5095.5
Exp/Cntr=0.3,0.1

Chan Stop Cuts=-1