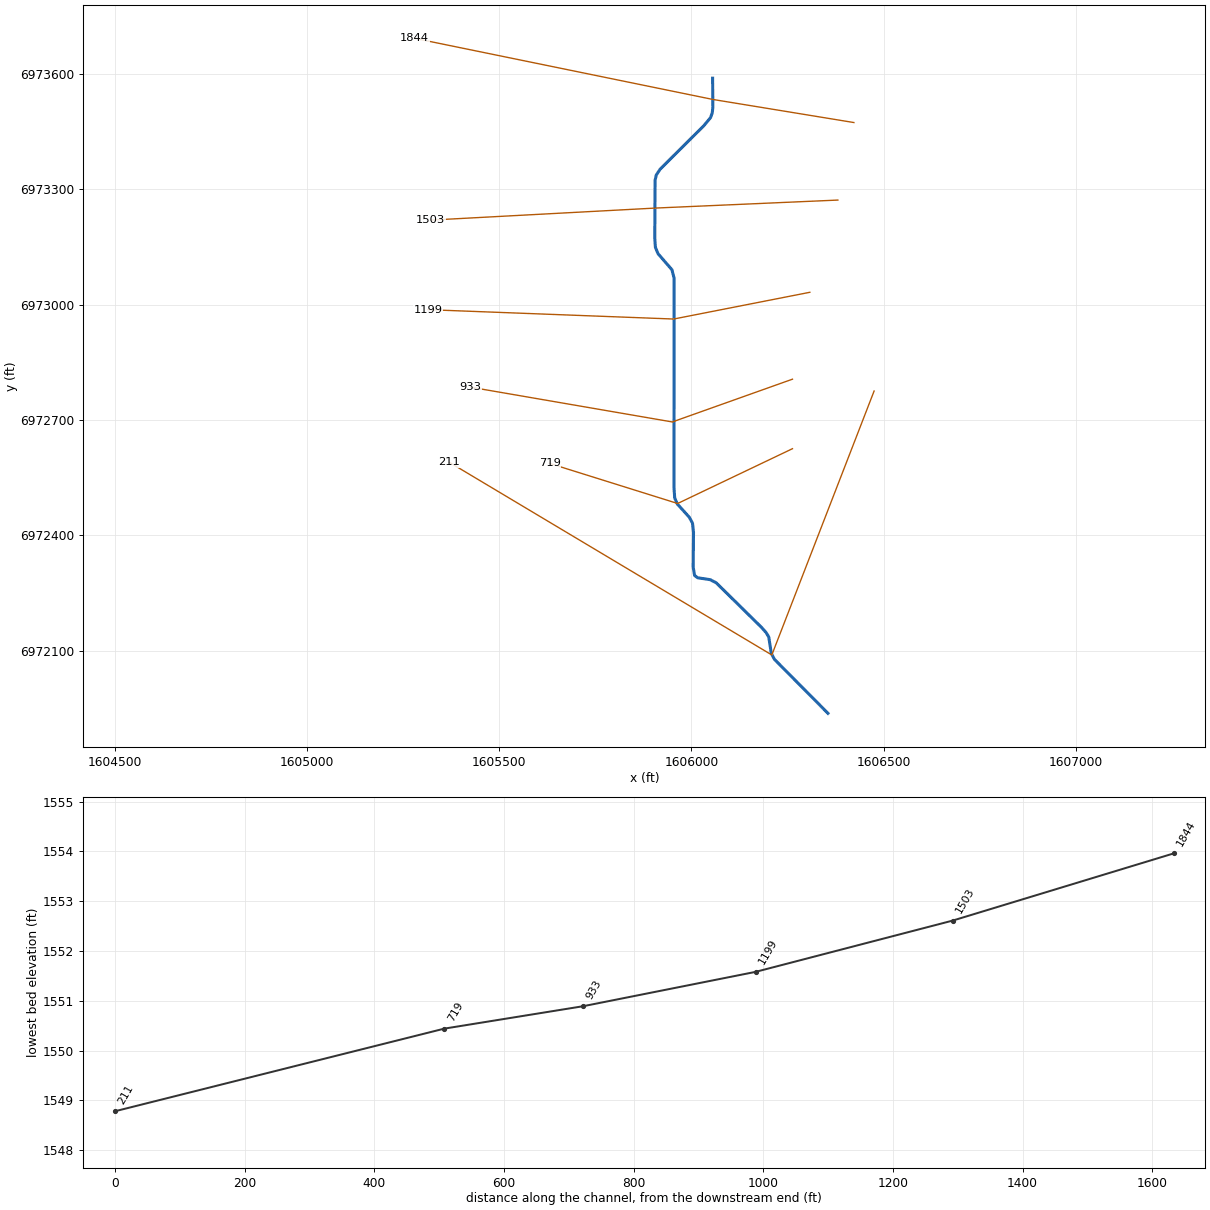
--- Chimney Creek 1122.prj (project) ---

Proj Title=Chimney Creek 1122 Base Level Engineering
Current Plan=p01
Default Exp/Contr=0.3,0.1
English Units
Geom File=g01
Flow File=f01
Plan File=p01
BEGIN DESCRIPTION:
Chimney Creek 1122
END DESCRIPTION:

--- Chimney Creek 1122.p01 (plan) ---

Plan Title=Multiple Run
Short Identifier=Multiple
Geom File=g01
Flow File=f01
Subcritical Flow
K Sum by GR= 0
Std Step Tol= 0.01
Critical Tol= 0.01
Num of Std Step Trials= 20
Max Error Tol= 0.3
Flow Tol Ratio= 0.001
Split Flow NTrial= 30
Split Flow Tol= 0.02
Split Flow Ratio= 0.02
Log Output Level= 0
Friction Slope Method= 1
Unsteady Friction Slope Method= 2
Unsteady Bridges Friction Slope Method= 1
Parabolic Critical Depth
Global Vel Dist=  1 , 1 , 1
Global Log Level= 0
CheckData=True
Encroach Param= -1, 0, 0, 0
BEGIN DESCRIPTION:
Multiple Run
END DESCRIPTION:

--- Chimney Creek 1122.f01 (steady flow) ---

Flow Title=Multiple
Number of Profiles=7
Profile Names=10-year,25-year,50-year,1pct_min,100-year,1pct_plu,500-year
River Rch & RM= Chimney Creek 11,Reach-1,1844
     204     275     333     201     400     799     586
Boundary for River Rch & Prof#=Chimney Creek 11,Reach-1,1
Up Type=0
Dn Type=3
Dn Slope=0.005
Boundary for River Rch & Prof#=Chimney Creek 11,Reach-1,2
Up Type=0
Dn Type=3
Dn Slope=0.005
Boundary for River Rch & Prof#=Chimney Creek 11,Reach-1,3
Up Type=0
Dn Type=3
Dn Slope=0.005
Boundary for River Rch & Prof#=Chimney Creek 11,Reach-1,4
Up Type=0
Dn Type=3
Dn Slope=0.005
Boundary for River Rch & Prof#=Chimney Creek 11,Reach-1,5
Up Type=0
Dn Type=3
Dn Slope=0.005
Boundary for River Rch & Prof#=Chimney Creek 11,Reach-1,6
Up Type=0
Dn Type=3
Dn Slope=0.005
Boundary for River Rch & Prof#=Chimney Creek 11,Reach-1,7
Up Type=0
Dn Type=3
Dn Slope=0.005

--- Chimney Creek 1122.g01 (geometry) ---

Geom Title=Existing Conditions

River Reach=Chimney Creek 11,Reach-1
Reach XY= 30
      1606055.00      6973588.00      1606055.59      6973512.75
      1606054.19      6973498.34      1606049.65      6973485.50
      1606032.12      6973464.48      1605918.37      6973351.32
      1605908.54      6973336.54      1605905.38      6973322.84
      1605904.57      6973172.82      1605906.22      6973148.51
      1605913.14      6973131.94      1605949.25      6973090.33
      1605954.93      6973067.97      1605954.56      6972524.18
      1605956.38      6972497.66      1605963.14      6972481.94
      1605994.14      6972447.64      1606002.72      6972432.05
      1606005.31      6972408.10      1606004.49      6972317.58
      1606008.08      6972296.31      1606016.00      6972290.20
      1606048.88      6972285.16      1606064.37      6972277.09
      1606181.99      6972161.47      1606194.22      6972147.68
      1606201.02      6972136.35      1606207.53      6972094.05
      1606215.77      6972078.32      1606355.00      6971938.00

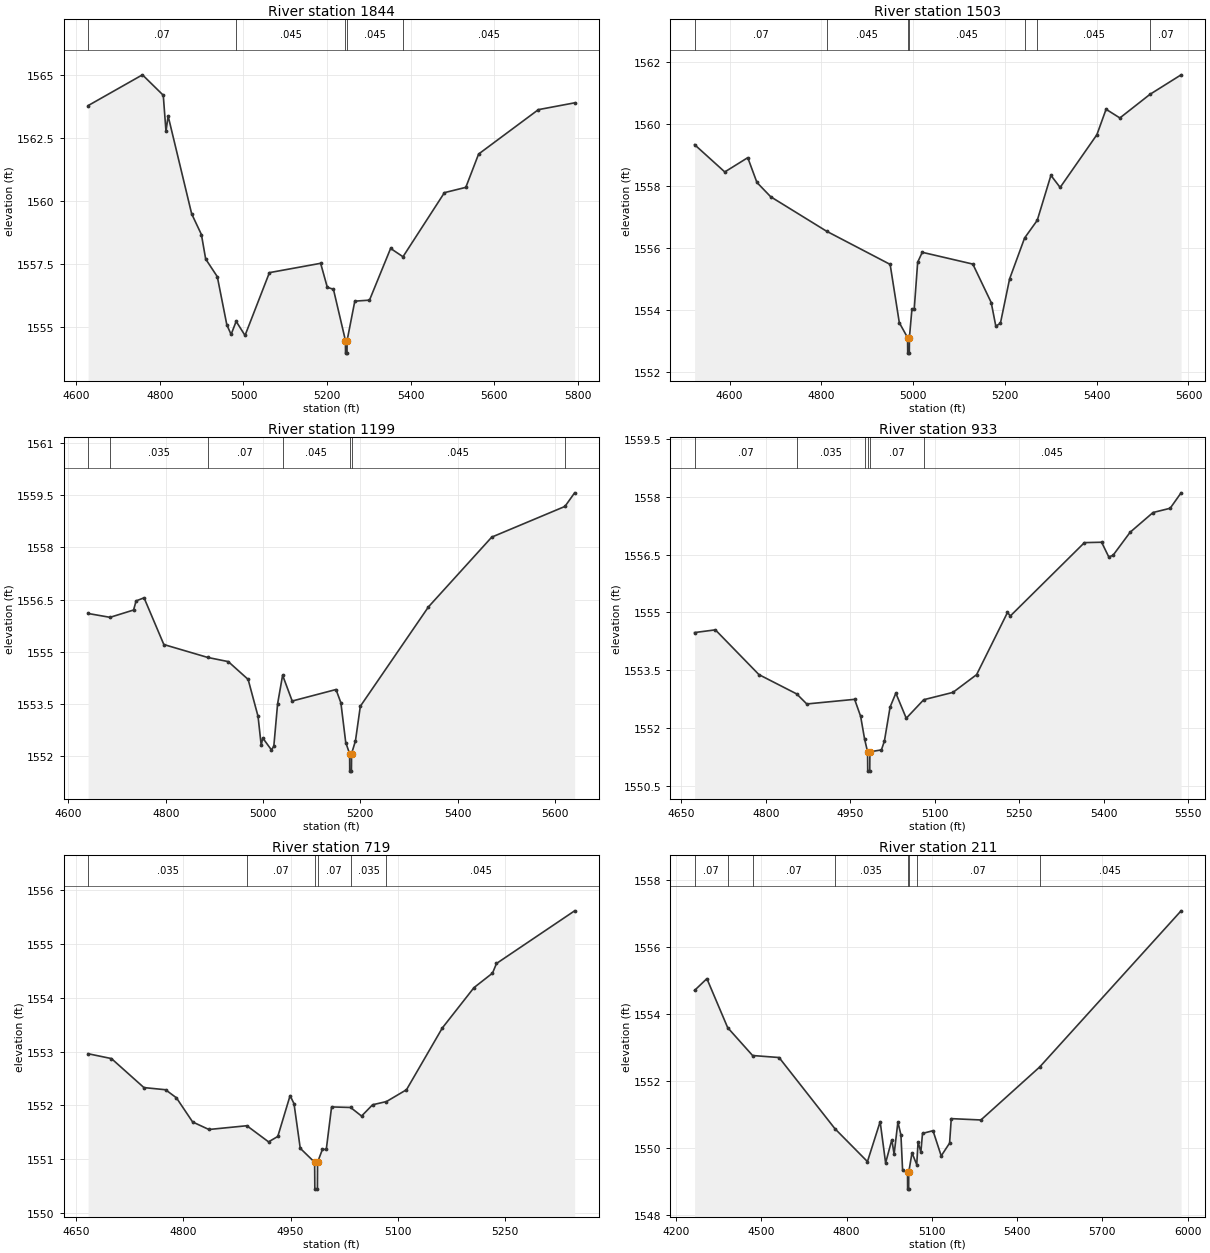
Type RM Length L Ch R = 1,1844,341,341,341
BEGIN DESCRIPTION:
Chimney Creek 1122 2.0
END DESCRIPTION:
XS GIS Cut Line= 3
      1606422.39      6973472.73      1606055.76      6973532.69
      1605280.04      6973691.48
#Sta/Elev= 30
  4628.5 1563.77  4758.4 1564.99  4808.2 1564.18  4814.7 1562.75  4819.8 1563.36
  4876.1 1559.48  4899.4 1558.66  4909.6 1557.69  4937.4 1556.99  4960.2 1555.08
  4970.4 1554.70  4982.5 1555.22  5003.7 1554.66  5062.0 1557.15  5184.5 1557.52
  5200.4 1556.57  5215.1 1556.49  5243.8 1554.46  5244.0 1553.96  5247.5 1553.96
  5247.8 1554.46  5266.2 1556.02  5301.3 1556.06  5351.8 1558.11  5381.4 1557.78
  5480.5 1560.32  5531.6 1560.53  5562.2 1561.85  5705.1 1563.61  5791.8 1563.88
#Mann=5,-1,0
  4628.5    0.07       0  4982.5   0.045       0  5243.8   0.045       0
  5247.8   0.045       0  5381.4   0.045       0
Bank Sta=5243.8,5247.8
Exp/Cntr=0.3,0.1

Type RM Length L Ch R = 1,1503,304,304,304
BEGIN DESCRIPTION:
Mapping XS 46795887
END DESCRIPTION:
XS GIS Cut Line= 3
      1606380.76      6973271.34      1605905.04      6973250.51
      1605321.75      6973219.26
#Sta/Elev= 30
  4523.6 1559.33  4589.4 1558.45  4639.5 1558.91  4659.5 1558.11  4689.5 1557.65
  4811.2 1556.54  4949.8 1555.47  4969.8 1553.59  4987.8 1553.11  4988.1 1552.61
  4991.6 1552.61  4991.8 1553.11  4997.3 1554.03  5002.3 1554.03  5009.8 1555.54
  5019.8 1555.86  5130.0 1555.48  5170.1 1554.24  5180.1 1553.48  5190.1 1553.57
  5210.1 1555.00  5242.8 1556.32  5270.4 1556.89  5300.2 1558.34  5320.3 1557.95
  5400.4 1559.65  5420.4 1560.47  5450.5 1560.19  5516.0 1560.95  5583.9 1561.58
#Mann=7,-1,0
  4523.6    0.07       0  4811.2   0.045       0  4987.8   0.045       0
  4991.8   0.045       0  5242.8   0.035       0  5270.4   0.045       0
  5516.0    0.07       0
Bank Sta=4987.8,4991.8
Exp/Cntr=0.3,0.1

Type RM Length L Ch R = 1,1199,266,266,266
BEGIN DESCRIPTION:
Mapping XS e86e141a
END DESCRIPTION:
XS GIS Cut Line= 3
      1606307.82      6973031.76      1605953.65      6972962.31
      1605314.73      6972986.62
#Sta/Elev= 30
  4640.5 1556.10  4685.6 1555.99  4734.0 1556.20  4739.1 1556.46  4755.5 1556.55
  4796.2 1555.21  4886.4 1554.84  4928.7 1554.72  4969.5 1554.21  4989.9 1553.15
  4996.4 1552.32  4999.6 1552.53  5017.3 1552.19  5022.3 1552.29  5030.1 1553.51
  5040.4 1554.33  5060.1 1553.59  5150.2 1553.92  5160.2 1553.54  5170.2 1552.40
  5178.2 1552.08  5178.4 1551.58  5181.9 1551.58  5182.2 1552.08  5190.2 1552.45
  5200.2 1553.44  5340.3 1556.29  5470.4 1558.29  5620.9 1559.17  5640.8 1559.56
#Mann=7,-1,0
  4640.5    0.07       0  4685.6   0.035       0  4886.4    0.07       0
  5040.4   0.045       0  5178.2    0.07       0  5182.2   0.045       0
  5620.9    0.07       0
Bank Sta=5178.2,5182.2
Exp/Cntr=0.3,0.1

Type RM Length L Ch R = 1,933,214,214,214
BEGIN DESCRIPTION:
Mapping XS 01aae90e
END DESCRIPTION:
XS GIS Cut Line= 3
      1606262.72      6972806.08      1605950.18      6972694.95
      1605425.90      6972785.22
#Sta/Elev= 30
  4673.4 1554.48  4710.3 1554.55  4787.7 1553.39  4854.7 1552.89  4872.6 1552.63
  4957.5 1552.75  4968.2 1552.31  4975.1 1551.73  4980.5 1551.39  4980.8 1550.89
  4984.4 1550.89  4984.6 1551.39  5005.1 1551.44  5010.4 1551.67  5020.5 1552.55
  5030.7 1552.91  5049.2 1552.26  5080.2 1552.74  5132.1 1552.93  5174.1 1553.39
  5228.9 1555.00  5234.0 1554.91  5365.5 1556.81  5396.0 1556.82  5408.7 1556.44
  5416.2 1556.48  5446.7 1557.08  5487.3 1557.59  5517.7 1557.70  5537.1 1558.10
#Mann=6,-1,0
  4673.4    0.07       0  4854.7   0.035       0  4975.1    0.07       0
  4980.5    0.07       0  4984.6    0.07       0  5080.2   0.045       0
Bank Sta=4980.5,4984.6
Exp/Cntr=0.3,0.1

Type RM Length L Ch R = 1,719,508,508,508
BEGIN DESCRIPTION:
Mapping XS 80285fee
END DESCRIPTION:
XS GIS Cut Line= 3
      1606262.64      6972625.49      1605964.07      6972483.14
      1605630.74      6972587.31
#Sta/Elev= 30
  4667.0 1552.96  4699.6 1552.87  4745.0 1552.33  4775.2 1552.29  4790.4 1552.14
  4813.1 1551.69  4835.8 1551.55  4888.9 1551.62  4919.2 1551.32  4932.1 1551.42
  4949.3 1552.18  4954.8 1552.03  4963.5 1551.20  4983.6 1550.94  4983.9 1550.44
  4987.5 1550.44  4987.7 1550.94  4994.5 1551.18  4999.9 1551.18  5007.3 1551.97
  5033.9 1551.96  5049.2 1551.80  5064.6 1552.01  5084.0 1552.07  5112.0 1552.29
  5162.1 1553.44  5206.3 1554.19  5232.2 1554.46  5237.8 1554.64  5347.0 1555.62
#Mann=6,-1,0
  4667.0   0.035       0  4888.9    0.07       0  4983.6    0.07       0
  4987.7    0.07       0  5033.9   0.035       0  5084.0   0.045       0
Bank Sta=4983.6,4987.7
Exp/Cntr=0.3,0.1

Type RM Length L Ch R = 1,211,0,0,0
BEGIN DESCRIPTION:
Chimney Creek 1122 1.0
END DESCRIPTION:
XS GIS Cut Line= 3
      1606474.93      6972775.27      1606208.97      6972089.65
      1605369.93      6972590.38
#Sta/Elev= 30
  4264.6 1554.70  4307.9 1555.05  4381.1 1553.59  4468.8 1552.76  4562.0 1552.70
  4758.6 1550.58  4873.1 1549.60  4917.8 1550.79  4937.0 1549.56  4958.9 1550.25
  4966.9 1549.82  4980.3 1550.78  4991.0 1550.39  4996.8 1549.34  5014.2 1549.28
  5014.5 1548.78  5018.1 1548.78  5018.4 1549.28  5029.9 1549.86  5046.6 1549.51
  5051.3 1550.19  5061.1 1549.88  5066.9 1550.44  5103.9 1550.52  5132.7 1549.77
  5162.2 1550.15  5168.1 1550.88  5272.5 1550.84  5479.6 1552.42  5977.1 1557.07
#Mann=8,-1,0
  4264.6    0.07       0  4381.1   0.035       0  4468.8    0.07       0
  4758.6   0.035       0  5014.2   0.035       0  5018.4   0.035       0
  5046.6    0.07       0  5479.6   0.045       0
Bank Sta=5014.2,5018.4
Exp/Cntr=0.3,0.1

Chan Stop Cuts=-1