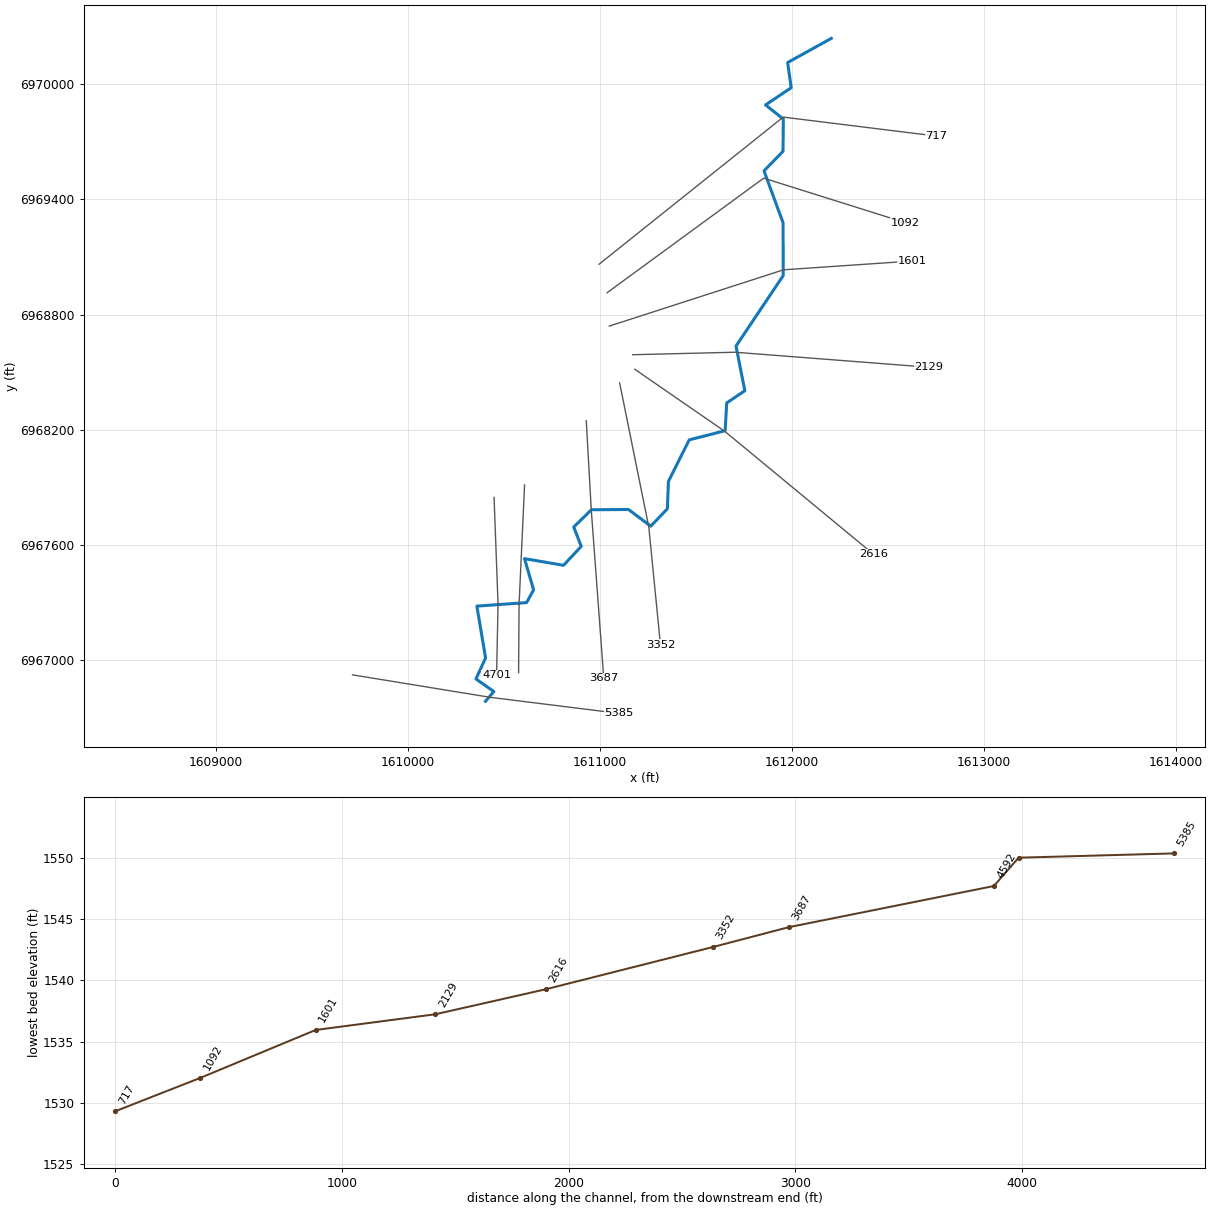
--- Chimney Creek 1123.prj (project) ---

Proj Title=Chimney Creek 1123 Base Level Engineering
Current Plan=p01
Default Exp/Contr=0.3,0.1
English Units
Geom File=g01
Flow File=f01
Plan File=p01
BEGIN DESCRIPTION:
Chimney Creek 1123
END DESCRIPTION:

--- Chimney Creek 1123.p01 (plan) ---

Plan Title=Multiple Run
Short Identifier=Multiple
Geom File=g01
Flow File=f01
Subcritical Flow
K Sum by GR= 0
Std Step Tol= 0.01
Critical Tol= 0.01
Num of Std Step Trials= 20
Max Error Tol= 0.3
Flow Tol Ratio= 0.001
Split Flow NTrial= 30
Split Flow Tol= 0.02
Split Flow Ratio= 0.02
Log Output Level= 0
Friction Slope Method= 1
Unsteady Friction Slope Method= 2
Unsteady Bridges Friction Slope Method= 1
Parabolic Critical Depth
Global Vel Dist=  1 , 1 , 1
Global Log Level= 0
CheckData=True
Encroach Param= -1, 0, 0, 0
BEGIN DESCRIPTION:
Multiple Run
END DESCRIPTION:

--- Chimney Creek 1123.f01 (steady flow) ---

Flow Title=Multiple
Number of Profiles=7
Profile Names=10-year,25-year,50-year,1pct_min,100-year,1pct_plu,500-year
River Rch & RM= Chimney Creek 11,Reach-1,5385
     191     258     311     187     373     743     542
River Rch & RM= Chimney Creek 11,Reach-1,3352
     223     304     368     223     444     886     654
Boundary for River Rch & Prof#=Chimney Creek 11,Reach-1,1
Up Type=0
Dn Type=3
Dn Slope=0.005
Boundary for River Rch & Prof#=Chimney Creek 11,Reach-1,2
Up Type=0
Dn Type=3
Dn Slope=0.005
Boundary for River Rch & Prof#=Chimney Creek 11,Reach-1,3
Up Type=0
Dn Type=3
Dn Slope=0.005
Boundary for River Rch & Prof#=Chimney Creek 11,Reach-1,4
Up Type=0
Dn Type=3
Dn Slope=0.005
Boundary for River Rch & Prof#=Chimney Creek 11,Reach-1,5
Up Type=0
Dn Type=3
Dn Slope=0.005
Boundary for River Rch & Prof#=Chimney Creek 11,Reach-1,6
Up Type=0
Dn Type=3
Dn Slope=0.005
Boundary for River Rch & Prof#=Chimney Creek 11,Reach-1,7
Up Type=0
Dn Type=3
Dn Slope=0.005

--- Chimney Creek 1123.g01 (geometry) ---

Geom Title=Existing Conditions

River Reach=Chimney Creek 11,Reach-1
Reach XY= 30
      1610405.00      6966788.00      1610448.50      6966838.28
      1610355.26      6966904.01      1610405.39      6967012.99
      1610360.00      6967283.00      1610618.81      6967301.22
      1610655.39      6967367.72      1610607.84      6967530.11
      1610811.08      6967495.47      1610903.35      6967594.04
      1610864.14      6967694.75      1610956.44      6967784.47
      1611149.15      6967785.93      1611265.03      6967698.95
      1611351.46      6967789.44      1611357.08      6967932.14
      1611465.36      6968148.16      1611652.08      6968195.92
      1611660.41      6968340.68      1611754.75      6968404.02
      1611708.73      6968636.47      1611954.49      6969003.21
      1611953.64      6969278.35      1611854.44      6969548.23
      1611953.36      6969649.84      1611954.93      6969817.81
      1611862.44      6969891.41      1611995.96      6969980.99
      1611977.51      6970111.95      1612205.00      6970238.00

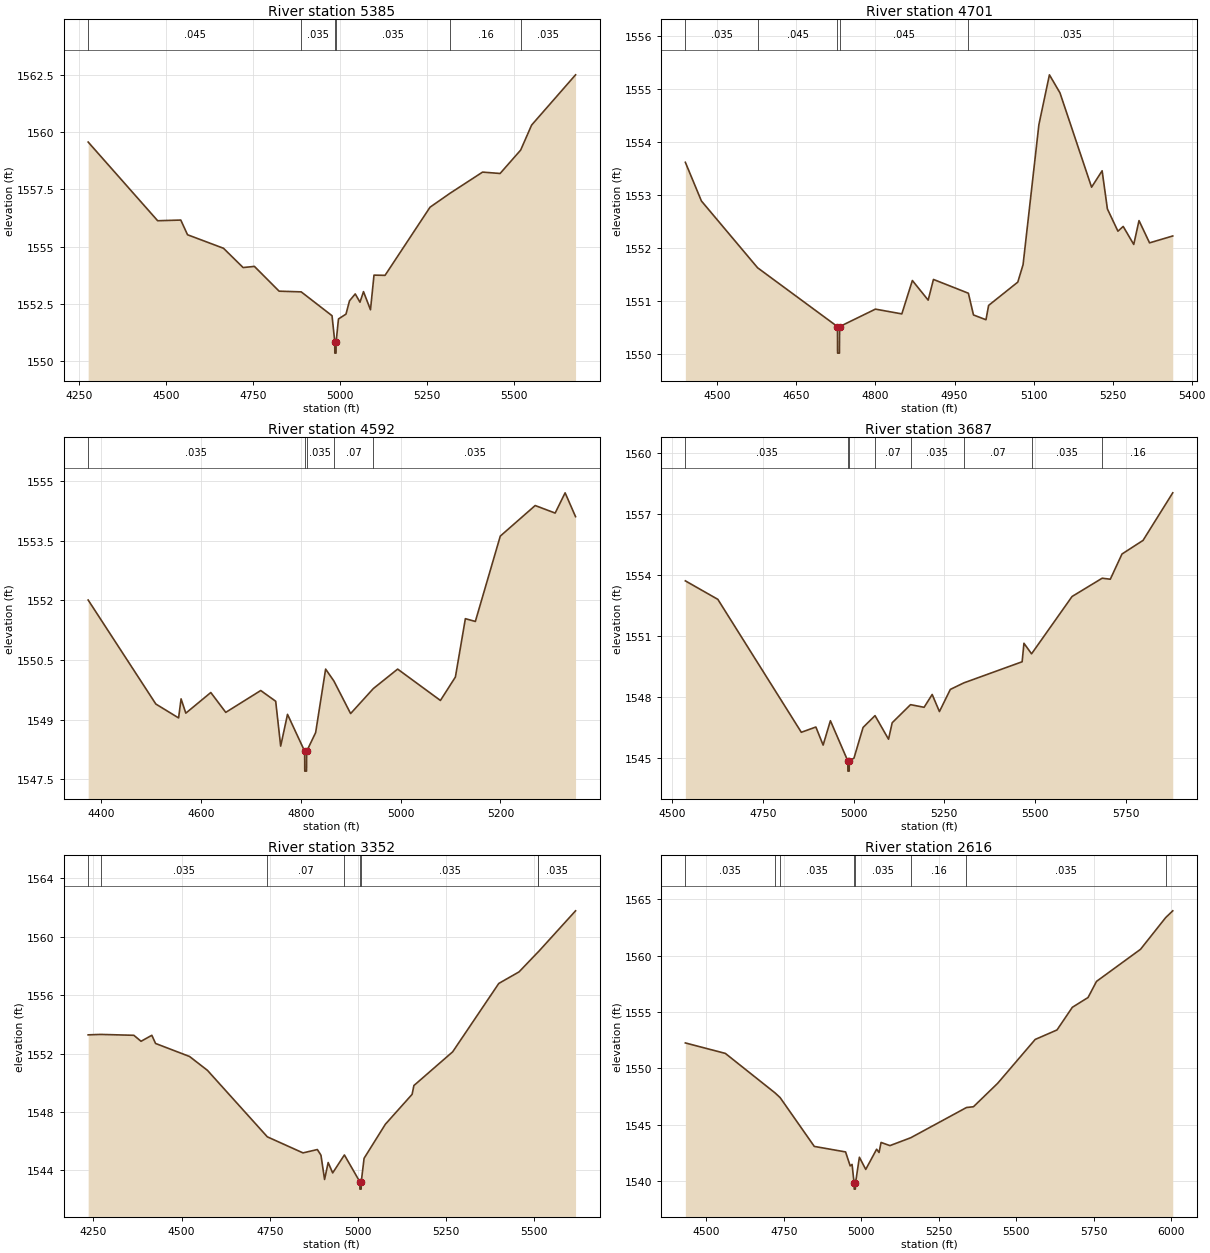
Type RM Length L Ch R = 1,5385,684,684,684
BEGIN DESCRIPTION:
Chimney Creek 1123 9.0
END DESCRIPTION:
XS GIS Cut Line= 3
      1609712.81      6966925.23      1610427.17      6966808.70
      1611100.45      6966724.76
#Sta/Elev= 30
  4276.2 1559.56  4476.2 1556.13  4542.7 1556.16  4562.1 1555.52  4665.6 1554.93
  4722.0 1554.09  4754.6 1554.14  4825.6 1553.06  4889.2 1553.03  4977.9 1551.99
  4985.7 1550.86  4985.9 1550.36  4989.4 1550.36  4989.7 1550.86  4996.4 1551.85
  5018.0 1552.06  5028.1 1552.64  5044.6 1552.94  5058.3 1552.58  5068.4 1553.04
  5088.5 1552.25  5098.6 1553.76  5130.4 1553.75  5259.8 1556.72  5317.6 1557.33
  5411.0 1558.25  5461.4 1558.19  5520.6 1559.21  5552.1 1560.30  5678.5 1562.49
#Mann=6,-1,0
  4276.2   0.045       0  4889.2   0.035       0  4985.7   0.035       0
  4989.7   0.035       0  5317.6    0.16       0  5520.6   0.035       0
Bank Sta=4985.7,4989.7
Exp/Cntr=0.3,0.1

Type RM Length L Ch R = 1,4701,109,109,109
BEGIN DESCRIPTION:
Mapping XS a6c25503
END DESCRIPTION:
XS GIS Cut Line= 3
      1610449.54      6967848.47      1610470.37      6967291.20
      1610462.56      6966924.04
#Sta/Elev= 30
  4439.2 1553.61  4469.7 1552.88  4576.3 1551.62  4727.9 1550.51  4728.1 1550.01
  4731.6 1550.01  4731.9 1550.51  4799.9 1550.84  4850.0 1550.75  4870.0 1551.38
  4900.0 1551.01  4910.0 1551.40  4976.3 1551.14  4986.0 1550.73  5009.7 1550.64
  5014.7 1550.91  5070.1 1551.35  5080.1 1551.68  5110.1 1554.32  5130.1 1555.26
  5150.1 1554.92  5210.1 1553.14  5230.1 1553.45  5240.1 1552.73  5260.1 1552.31
  5270.1 1552.40  5290.1 1552.06  5300.1 1552.51  5320.1 1552.09  5364.1 1552.22
#Mann=5,-1,0
  4439.2   0.035       0  4576.3   0.045       0  4727.9   0.035       0
  4731.9   0.045       0  4976.3   0.035       0
Bank Sta=4727.9,4731.9
Exp/Cntr=0.3,0.1

Type RM Length L Ch R = 1,4592,905,905,905
BEGIN DESCRIPTION:
Mapping XS 19bfad42
END DESCRIPTION:
XS GIS Cut Line= 3
      1610608.39      6967913.59      1610579.75      6967293.81
      1610577.14      6966937.06
#Sta/Elev= 30
  4373.4 1552.01  4509.1 1549.39  4554.7 1549.04  4559.7 1549.52  4569.2 1549.16
  4619.3 1549.68  4649.3 1549.18  4719.4 1549.73  4749.4 1549.46  4759.4 1548.33
  4773.1 1549.13  4807.5 1548.20  4807.7 1547.70  4811.2 1547.70  4811.5 1548.20
  4829.5 1548.67  4849.5 1550.27  4866.1 1549.97  4899.6 1549.15  4945.2 1549.78
  4993.9 1550.27  5079.7 1549.48  5109.7 1550.07  5129.7 1551.54  5149.7 1551.47
  5199.7 1553.62  5269.7 1554.39  5309.7 1554.20  5329.7 1554.71  5350.6 1554.11
#Mann=5,-1,0
  4373.4   0.035       0  4807.5   0.035       0  4811.5   0.035       0
  4866.1    0.07       0  4945.2   0.035       0
Bank Sta=4807.5,4811.5
Exp/Cntr=0.3,0.1

Type RM Length L Ch R = 1,3687,335,335,335
BEGIN DESCRIPTION:
Mapping XS 162cfed5
END DESCRIPTION:
XS GIS Cut Line= 3
      1610929.43      6968247.44      1610955.47      6967783.06
      1611020.58      6966906.28
#Sta/Elev= 30
  4535.8 1553.70  4625.4 1552.79  4855.7 1546.25  4895.8 1546.51  4915.8 1545.62
  4935.9 1546.82  4983.9 1544.84  4984.2 1544.34  4987.7 1544.34  4987.9 1544.84
  5000.9 1544.98  5026.0 1546.49  5059.0 1547.07  5096.2 1545.91  5106.3 1546.72
  5156.9 1547.61  5194.3 1547.48  5216.6 1548.11  5236.6 1547.27  5266.7 1548.36
  5303.8 1548.68  5464.7 1549.72  5469.7 1550.63  5490.7 1550.11  5602.4 1552.93
  5685.5 1553.83  5707.9 1553.78  5740.1 1555.02  5798.2 1555.69  5880.1 1558.03
#Mann=8,-1,0
  4535.8   0.035       0  4983.9   0.035       0  4987.9   0.035       0
  5059.0    0.07       0  5156.9   0.035       0  5303.8    0.07       0
  5490.7   0.035       0  5685.5    0.16       0
Bank Sta=4983.9,4987.9
Exp/Cntr=0.3,0.1

Type RM Length L Ch R = 1,3352,736,736,736
BEGIN DESCRIPTION:
Mapping XS b1fc4fdc
END DESCRIPTION:
XS GIS Cut Line= 3
      1611103.04      6968444.93      1611254.95      6967694.09
      1611315.56      6967081.43
#Sta/Elev= 30
  4235.0 1553.28  4270.4 1553.31  4364.5 1553.25  4384.9 1552.84  4415.5 1553.25
  4426.1 1552.69  4522.4 1551.80  4573.2 1550.85  4742.9 1546.30  4844.0 1545.20
  4884.8 1545.43  4895.0 1545.04  4905.2 1543.38  4915.4 1544.54  4928.2 1543.83
  4961.4 1545.06  5005.2 1543.22  5005.4 1542.72  5008.9 1542.72  5009.2 1543.22
  5017.2 1544.83  5077.5 1547.16  5153.4 1549.21  5158.4 1549.81  5268.4 1552.12
  5399.1 1556.80  5456.5 1557.59  5510.4 1558.95  5511.4 1558.97  5616.7 1561.77
#Mann=8,-1,0
  4235.0    0.07       0  4270.4   0.035       0  4742.9    0.07       0
  4961.4   0.035       0  5005.2   0.035       0  5009.2   0.035       0
  5510.4    0.16       0  5511.4   0.035       0
Bank Sta=5005.2,5009.2
Exp/Cntr=0.3,0.1

Type RM Length L Ch R = 1,2616,487,487,487
BEGIN DESCRIPTION:
Mapping XS 229566f5
END DESCRIPTION:
XS GIS Cut Line= 3
      1611182.29      6968515.43      1611651.07      6968192.06
      1612425.11      6967552.45
#Sta/Elev= 30
  4432.0 1552.25  4561.2 1551.32  4721.9 1547.81  4738.0 1547.40  4848.3 1543.07
  4949.3 1542.58  4964.2 1541.34  4970.3 1541.47  4977.0 1539.78  4977.3 1539.28
  4980.9 1539.28  4981.2 1539.78  4993.9 1542.11  5014.4 1541.03  5049.6 1542.82
  5057.4 1542.53  5063.9 1543.42  5092.6 1543.14  5159.9 1543.84  5339.7 1546.52
  5362.2 1546.59  5440.4 1548.67  5561.5 1552.56  5631.9 1553.40  5681.4 1555.41
  5732.2 1556.28  5759.5 1557.71  5901.7 1560.56  5982.5 1563.36  6005.6 1563.97
#Mann=8,-1,0
  4432.0   0.035       0  4721.9    0.07       0  4738.0   0.035       0
  4977.0   0.035       0  4981.2   0.035       0  5159.9    0.16       0
  5339.7   0.035       0  5982.5    0.07       0
Bank Sta=4977,4981.2
Exp/Cntr=0.3,0.1

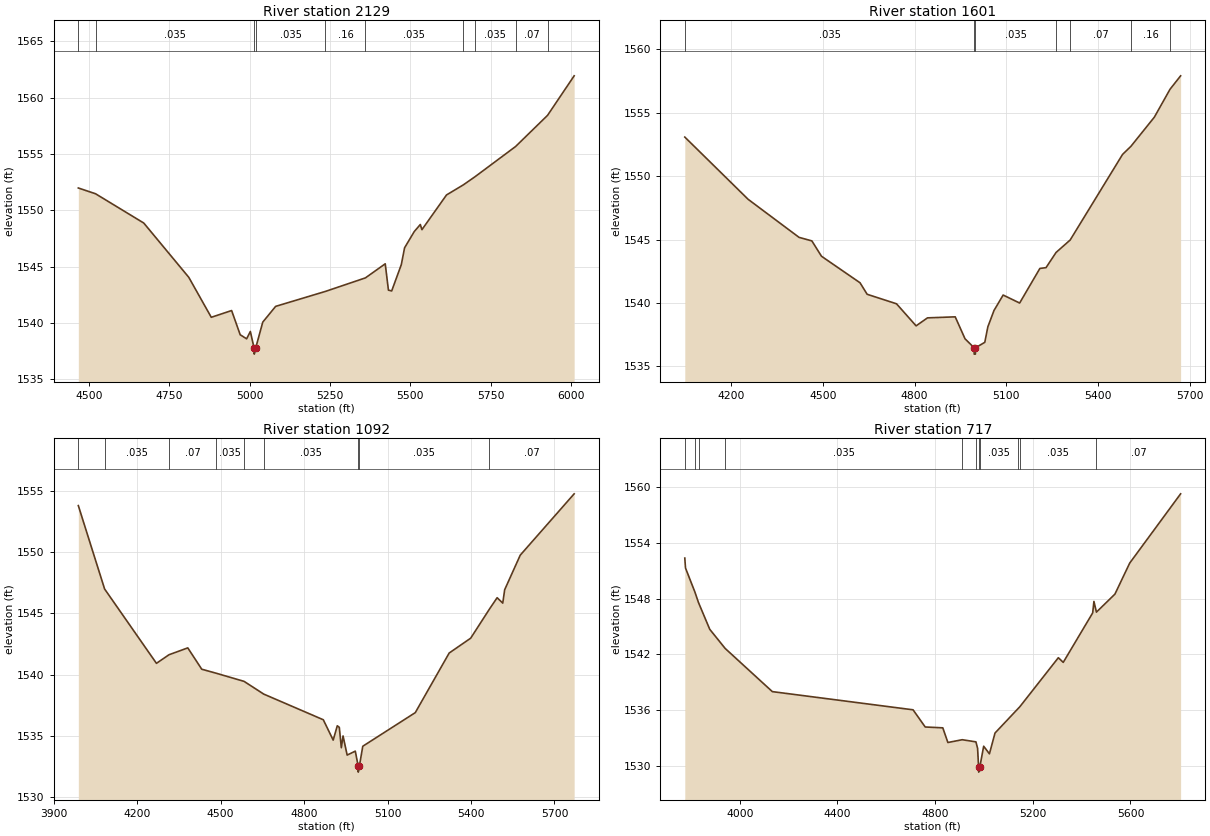
Type RM Length L Ch R = 1,2129,528,528,528
BEGIN DESCRIPTION:
Mapping XS 421252da
END DESCRIPTION:
XS GIS Cut Line= 3
      1611171.42      6968591.37      1611703.15      6968604.39
      1612711.15      6968526.35
#Sta/Elev= 30
  4466.7 1551.99  4520.2 1551.48  4670.3 1548.88  4810.4 1544.06  4880.4 1540.51
  4943.7 1541.11  4970.4 1538.96  4990.4 1538.60  5002.0 1539.25  5013.9 1537.74
  5014.2 1537.24  5018.2 1537.74  5040.6 1540.08  5080.7 1541.48  5235.8 1542.81
  5360.1 1544.01  5421.7 1545.26  5431.7 1542.92  5441.8 1542.85  5471.8 1545.19
  5481.9 1546.68  5512.0 1548.12  5530.9 1548.75  5535.9 1548.29  5612.3 1551.37
  5664.8 1552.27  5700.6 1552.98  5827.2 1555.67  5926.8 1558.44  6009.6 1561.95
#Mann=10,-1,0
  4466.7    0.07       0  4520.2   0.035       0  5013.9   0.035       0
  5018.2   0.035       0  5235.8    0.16       0  5360.1   0.035       0
  5664.8    0.07       0  5700.6   0.035       0  5827.2    0.07       0
  5926.8   0.035       0
Bank Sta=5013.9,5018.2
Exp/Cntr=0.3,0.1

Type RM Length L Ch R = 1,1601,509,509,509
BEGIN DESCRIPTION:
Mapping XS 17a55031
END DESCRIPTION:
XS GIS Cut Line= 3
      1611049.12      6968740.40      1611956.19      6969033.35
      1612624.63      6969078.93
#Sta/Elev= 30
  4047.6 1553.08  4255.0 1548.17  4421.6 1545.17  4463.6 1544.89  4495.1 1543.68
  4621.2 1541.59  4644.6 1540.68  4740.7 1539.93  4804.8 1538.19  4842.1 1538.82
  4932.9 1538.90  4965.0 1537.17  4994.8 1536.46  4995.1 1535.96  4998.9 1535.96
  4999.1 1536.46  5029.7 1536.89  5039.7 1538.11  5059.8 1539.40  5089.8 1540.62
  5143.8 1539.99  5210.1 1542.72  5230.1 1542.78  5263.1 1543.98  5309.2 1544.96
  5480.7 1551.71  5508.1 1552.35  5584.8 1554.65  5636.1 1556.85  5670.8 1557.91
#Mann=7,-1,0
  4047.6   0.035       0  4994.8   0.035       0  4999.1   0.035       0
  5263.1    0.16       0  5309.2    0.07       0  5508.1    0.16       0
  5636.1    0.07       0
Bank Sta=4994.8,4999.1
Exp/Cntr=0.3,0.1

Type RM Length L Ch R = 1,1092,375,375,375
BEGIN DESCRIPTION:
Mapping XS 9e90b792
END DESCRIPTION:
XS GIS Cut Line= 3
      1611037.81      6968914.01      1611852.89      6969510.35
      1612589.86      6969278.58
#Sta/Elev= 30
  3988.3 1553.78  4082.8 1546.98  4269.1 1540.92  4314.2 1541.62  4381.8 1542.18
  4432.0 1540.44  4482.9 1540.12  4584.1 1539.45  4655.0 1538.41  4869.0 1536.32
  4904.5 1534.66  4919.2 1535.83  4926.5 1535.70  4933.8 1534.04  4940.0 1535.00
  4954.7 1533.44  4984.0 1533.76  4994.3 1532.55  4994.6 1532.05  4998.7 1532.55
  5010.9 1534.16  5199.6 1536.90  5321.5 1541.76  5398.8 1542.97  5466.2 1545.34
  5493.9 1546.27  5514.1 1545.83  5521.0 1546.92  5577.0 1549.74  5770.8 1554.74
#Mann=9,-1,0
  3988.3    0.07       0  4082.8   0.035       0  4314.2    0.07       0
  4482.9   0.035       0  4584.1    0.07       0  4655.0   0.035       0
  4994.3   0.035       0  4998.7   0.035       0  5466.2    0.07       0
Bank Sta=4994.3,4998.7
Exp/Cntr=0.3,0.1

Type RM Length L Ch R = 1,717,0,0,0
BEGIN DESCRIPTION:
Mapping XS 2a001843
END DESCRIPTION:
XS GIS Cut Line= 3
      1610996.11      6969062.43      1611954.46      6969828.06
      1612751.94      6969729.35
#Sta/Elev= 30
  3775.2 1552.38  3778.1 1551.31  3816.5 1548.73  3831.3 1547.59  3877.4 1544.71
  3940.5 1542.65  4133.6 1538.00  4709.9 1536.04  4759.6 1534.19  4831.6 1534.10
  4852.4 1532.52  4911.2 1532.82  4967.2 1532.59  4974.1 1531.89  4978.3 1529.83
  4978.6 1529.33  4982.8 1529.83  4999.0 1532.12  5022.5 1531.30  5045.4 1533.54
  5141.2 1536.21  5146.1 1536.34  5304.7 1541.65  5324.8 1541.15  5445.4 1546.48
  5450.4 1547.71  5460.7 1546.56  5536.4 1548.50  5596.9 1551.84  5805.4 1559.30
#Mann=11,-1,0
  3775.2    0.07       0  3816.5   0.035       0  3831.3    0.07       0
  3940.5   0.035       0  4911.2    0.07       0  4967.2   0.035       0
  4978.3   0.035       0  4982.8   0.035       0  5141.2    0.07       0
  5146.1   0.035       0  5460.7    0.07       0
Bank Sta=4978.3,4982.8
Exp/Cntr=0.3,0.1

Chan Stop Cuts=-1