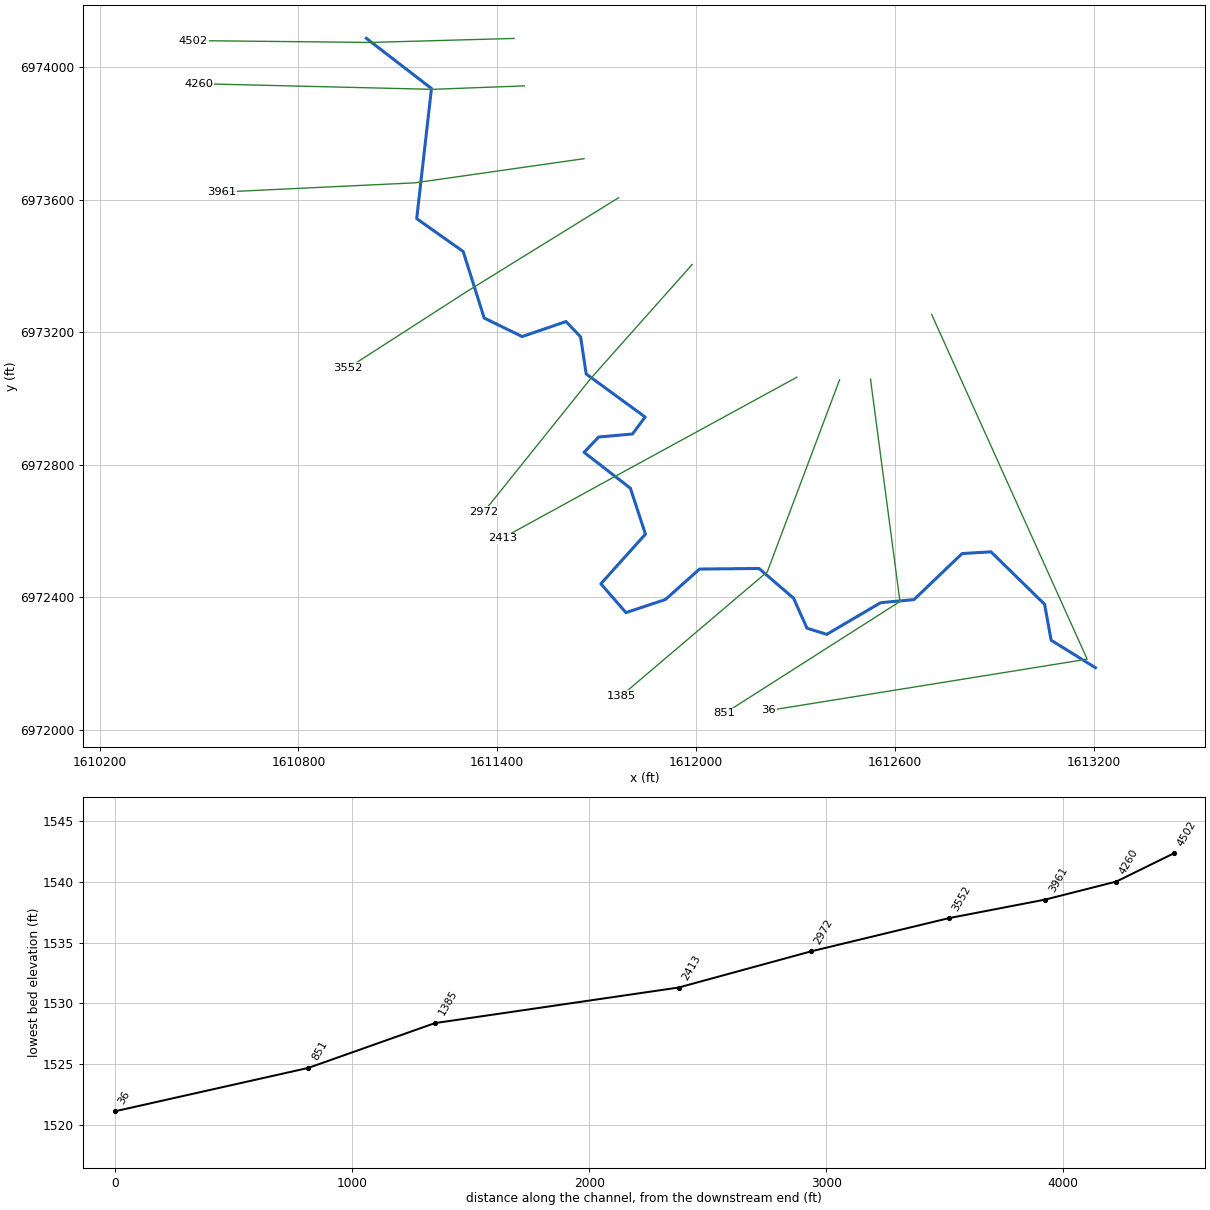
--- Chimney Creek 1124.prj (project) ---

Proj Title=Chimney Creek 1124 Base Level Engineering
Current Plan=p01
Default Exp/Contr=0.3,0.1
English Units
Geom File=g01
Flow File=f01
Plan File=p01
BEGIN DESCRIPTION:
Chimney Creek 1124
END DESCRIPTION:

--- Chimney Creek 1124.p01 (plan) ---

Plan Title=Multiple Run
Short Identifier=Multiple
Geom File=g01
Flow File=f01
Subcritical Flow
K Sum by GR= 0
Std Step Tol= 0.01
Critical Tol= 0.01
Num of Std Step Trials= 20
Max Error Tol= 0.3
Flow Tol Ratio= 0.001
Split Flow NTrial= 30
Split Flow Tol= 0.02
Split Flow Ratio= 0.02
Log Output Level= 0
Friction Slope Method= 1
Unsteady Friction Slope Method= 2
Unsteady Bridges Friction Slope Method= 1
Parabolic Critical Depth
Global Vel Dist=  1 , 1 , 1
Global Log Level= 0
CheckData=True
Encroach Param= -1, 0, 0, 0
BEGIN DESCRIPTION:
Multiple Run
END DESCRIPTION:

--- Chimney Creek 1124.f01 (steady flow) ---

Flow Title=Multiple
Number of Profiles=7
Profile Names=10-year,25-year,50-year,1pct_min,100-year,1pct_plu,500-year
River Rch & RM= Chimney Creek 11,Reach-1,4502
     212     289     351     213     425     847     629
River Rch & RM= Chimney Creek 11,Reach-1,2413
     247     339     414     252     502    1002     750
Boundary for River Rch & Prof#=Chimney Creek 11,Reach-1,1
Up Type=0
Dn Type=3
Dn Slope=0.005
Boundary for River Rch & Prof#=Chimney Creek 11,Reach-1,2
Up Type=0
Dn Type=3
Dn Slope=0.005
Boundary for River Rch & Prof#=Chimney Creek 11,Reach-1,3
Up Type=0
Dn Type=3
Dn Slope=0.005
Boundary for River Rch & Prof#=Chimney Creek 11,Reach-1,4
Up Type=0
Dn Type=3
Dn Slope=0.005
Boundary for River Rch & Prof#=Chimney Creek 11,Reach-1,5
Up Type=0
Dn Type=3
Dn Slope=0.005
Boundary for River Rch & Prof#=Chimney Creek 11,Reach-1,6
Up Type=0
Dn Type=3
Dn Slope=0.005
Boundary for River Rch & Prof#=Chimney Creek 11,Reach-1,7
Up Type=0
Dn Type=3
Dn Slope=0.005

--- Chimney Creek 1124.g01 (geometry) ---

Geom Title=Existing Conditions

River Reach=Chimney Creek 11,Reach-1
Reach XY= 30
      1611005.00      6974088.00      1611201.47      6973936.55
      1611156.97      6973543.68      1611297.25      6973444.45
      1611360.58      6973243.57      1611475.16      6973187.71
      1611607.58      6973233.03      1611651.47      6973186.78
      1611668.39      6973074.67      1611846.23      6972944.78
      1611808.00      6972893.54      1611706.01      6972884.39
      1611661.97      6972838.23      1611801.68      6972729.95
      1611847.13      6972591.22      1611712.59      6972441.31
      1611788.22      6972354.28      1611907.28      6972393.82
      1612010.45      6972485.82      1612189.85      6972487.62
      1612294.22      6972397.68      1612334.53      6972307.27
      1612394.25      6972288.68      1612556.59      6972384.17
      1612657.43      6972393.52      1612802.57      6972532.60
      1612889.79      6972537.77      1613051.50      6972379.52
      1613071.29      6972270.88      1613205.00      6972188.00

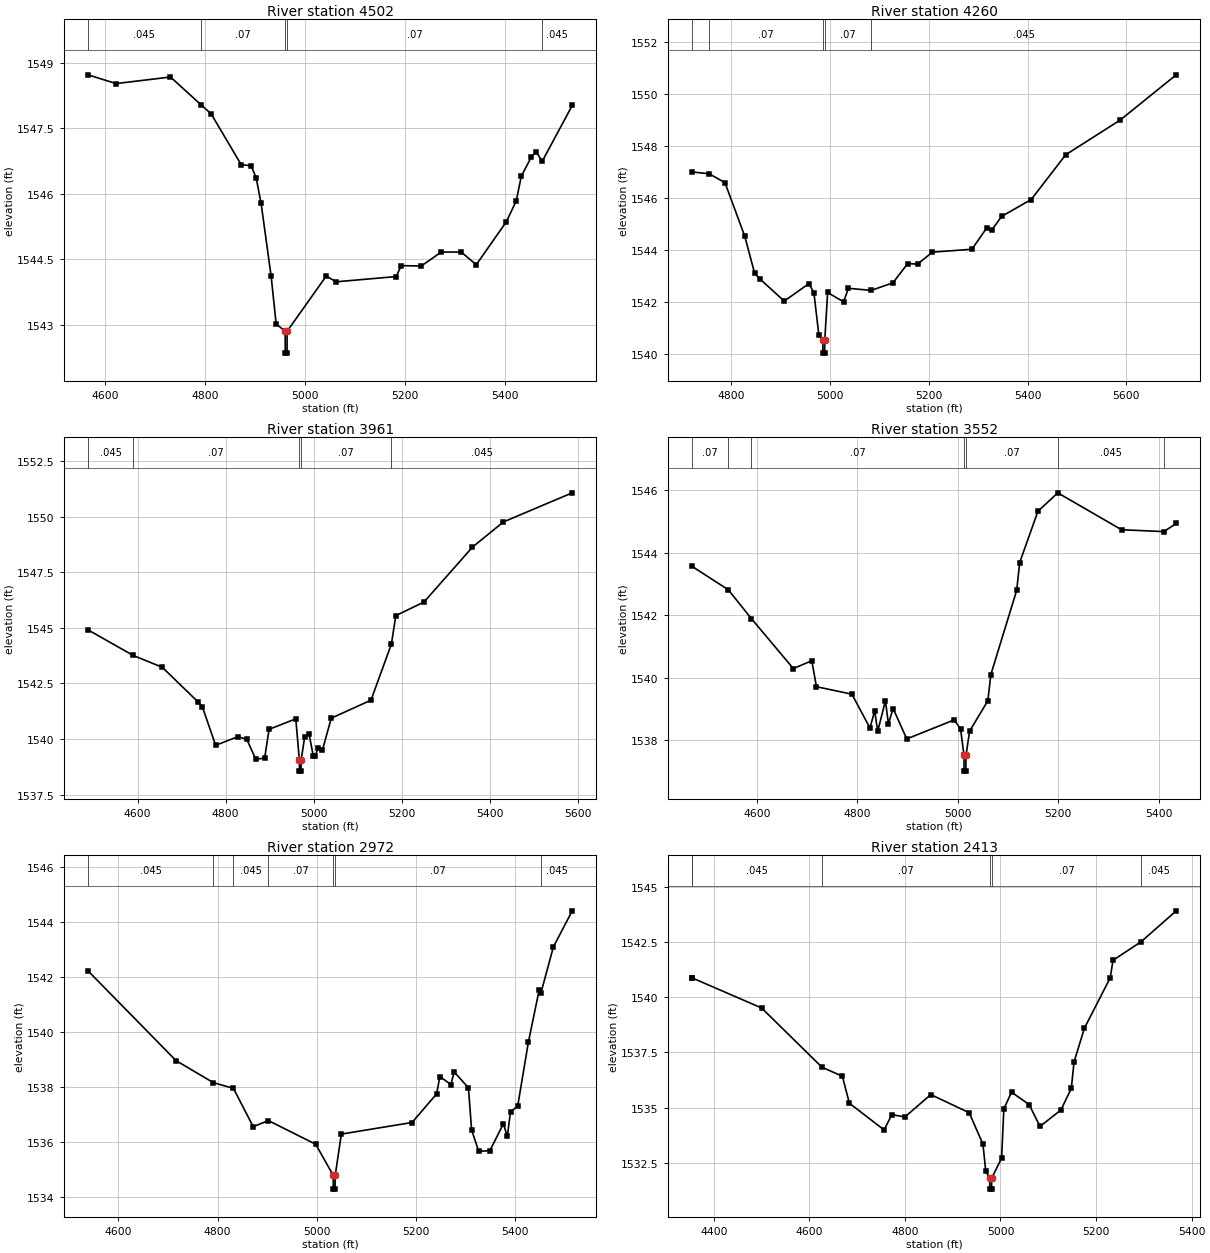
Type RM Length L Ch R = 1,4502,242,242,242
BEGIN DESCRIPTION:
Chimney Creek 1124 3.0
END DESCRIPTION:
XS GIS Cut Line= 3
      1611450.99      6974087.69      1611016.85      6974075.61
      1610483.08      6974081.18
#Sta/Elev= 30
  4565.7 1548.72  4621.7 1548.52  4730.6 1548.67  4791.2 1548.04  4811.8 1547.83
  4871.8 1546.67  4891.8 1546.64  4901.8 1546.37  4911.8 1545.78  4931.8 1544.12
  4941.8 1543.03  4959.8 1542.86  4960.1 1542.36  4963.6 1542.36  4963.8 1542.86
  5041.9 1544.12  5061.9 1543.99  5181.9 1544.11  5191.9 1544.36  5231.9 1544.35
  5271.9 1544.67  5311.9 1544.67  5341.9 1544.38  5401.9 1545.36  5421.9 1545.84
  5431.9 1546.40  5451.9 1546.84  5461.9 1546.96  5473.6 1546.74  5533.8 1548.02
#Mann=5,-1,0
  4565.7   0.045       0  4791.2    0.07       0  4959.8    0.07       0
  4963.8    0.07       0  5473.6   0.045       0
Bank Sta=4959.8,4963.8
Exp/Cntr=0.3,0.1

Type RM Length L Ch R = 1,4260,299,299,299
BEGIN DESCRIPTION:
Mapping XS f1746b5d
END DESCRIPTION:
XS GIS Cut Line= 3
      1611481.80      6973944.46      1611204.44      6973934.05
      1610501.30      6973950.97
#Sta/Elev= 30
  4720.3 1547.00  4755.0 1546.93  4787.1 1546.59  4827.2 1544.53  4847.2 1543.11
  4857.2 1542.90  4907.2 1542.04  4957.3 1542.71  4967.3 1542.36  4977.3 1540.74
  4985.3 1540.54  4985.5 1540.04  4989.0 1540.04  4989.3 1540.54  4995.1 1542.37
  5027.3 1542.01  5037.3 1542.53  5083.4 1542.45  5127.3 1542.74  5157.3 1543.48
  5177.3 1543.46  5207.4 1543.92  5287.4 1544.03  5317.4 1544.85  5327.4 1544.76
  5347.4 1545.29  5407.4 1545.94  5477.4 1547.66  5587.5 1548.99  5701.2 1550.73
#Mann=5,-1,0
  4720.3   0.045       0  4755.0    0.07       0  4985.3    0.07       0
  4989.3    0.07       0  5083.4   0.045       0
Bank Sta=4985.3,4989.3
Exp/Cntr=0.3,0.1

Type RM Length L Ch R = 1,3961,409,409,409
BEGIN DESCRIPTION:
Mapping XS 0c6e0549
END DESCRIPTION:
XS GIS Cut Line= 3
      1611661.69      6973724.67      1611151.24      6973651.75
      1610568.93      6973624.02
#Sta/Elev= 30
  4487.7 1544.91  4590.2 1543.76  4656.1 1543.23  4736.9 1541.68  4747.0 1541.46
  4777.3 1539.72  4827.8 1540.11  4848.0 1539.99  4868.2 1539.10  4888.4 1539.14
  4898.5 1540.44  4959.1 1540.91  4967.2 1539.06  4967.5 1538.56  4971.0 1538.56
  4971.2 1539.06  4979.3 1540.09  4989.4 1540.22  4998.9 1539.22  5003.3 1539.22
  5009.6 1539.62  5019.6 1539.51  5039.6 1540.94  5129.7 1541.75  5176.0 1544.27
  5186.0 1545.55  5249.9 1546.16  5360.0 1548.63  5430.1 1549.76  5586.3 1551.07
#Mann=5,-1,0
  4487.7   0.045       0  4590.2    0.07       0  4967.2    0.07       0
  4971.2    0.07       0  5176.0   0.045       0
Bank Sta=4967.2,4971.2
Exp/Cntr=0.3,0.1

Type RM Length L Ch R = 1,3552,580,580,580
BEGIN DESCRIPTION:
Mapping XS fc2696d1
END DESCRIPTION:
XS GIS Cut Line= 3
      1611765.80      6973606.60      1611310.96      6973325.36
      1610950.12      6973092.90
#Sta/Elev= 30
  4470.9 1543.57  4543.2 1542.82  4589.0 1541.90  4672.7 1540.30  4709.4 1540.55
  4718.7 1539.72  4789.3 1539.48  4825.2 1538.40  4834.7 1538.95  4840.6 1538.29
  4856.0 1539.27  4861.9 1538.54  4871.4 1539.02  4898.5 1538.05  4993.1 1538.66
  5005.7 1538.36  5012.4 1537.52  5012.6 1537.02  5016.1 1537.02  5016.4 1537.52
  5023.6 1538.30  5059.9 1539.27  5065.9 1540.11  5117.3 1542.80  5123.3 1543.69
  5159.6 1545.33  5199.1 1545.92  5326.0 1544.74  5410.3 1544.68  5434.9 1544.94
#Mann=7,-1,0
  4470.9    0.07       0  4543.2   0.045       0  4589.0    0.07       0
  5012.4    0.07       0  5016.4    0.07       0  5199.1   0.045       0
  5410.3   0.035       0
Bank Sta=5012.4,5016.4
Exp/Cntr=0.3,0.1

Type RM Length L Ch R = 1,2972,559,559,559
BEGIN DESCRIPTION:
Mapping XS 7e3ced56
END DESCRIPTION:
XS GIS Cut Line= 3
      1611988.08      6973405.26      1611682.49      6973061.47
      1611359.77      6972658.94
#Sta/Elev= 30
  4538.8 1542.22  4716.1 1538.96  4791.2 1538.16  4831.9 1537.95  4871.7 1536.56
  4902.4 1536.78  4997.7 1535.92  5033.0 1534.79  5033.2 1534.29  5036.7 1534.29
  5037.0 1534.79  5049.4 1536.29  5191.8 1536.71  5241.4 1537.75  5247.9 1538.38
  5270.2 1538.09  5276.7 1538.55  5305.5 1537.97  5311.9 1536.44  5326.3 1535.66
  5348.7 1535.69  5375.9 1536.66  5383.9 1536.21  5390.3 1537.10  5404.7 1537.30
  5426.2 1539.62  5447.9 1541.51  5451.8 1541.43  5476.7 1543.09  5514.7 1544.40
#Mann=7,-1,0
  4538.8   0.045       0  4791.2    0.07       0  4831.9   0.045       0
  4902.4    0.07       0  5033.0    0.07       0  5037.0    0.07       0
  5451.8   0.045       0
Bank Sta=5033,5037
Exp/Cntr=0.3,0.1

Type RM Length L Ch R = 1,2413,1028,1028,1028
BEGIN DESCRIPTION:
Mapping XS b5688d87
END DESCRIPTION:
XS GIS Cut Line= 3
      1612304.05      6973064.96      1611738.04      6972755.91
      1611415.10      6972578.82
#Sta/Elev= 30
  4354.5 1540.87  4355.2 1540.87  4500.3 1539.51  4626.4 1536.83  4669.2 1536.42
  4683.8 1535.20  4756.5 1533.99  4772.6 1534.68  4800.1 1534.58  4854.2 1535.59
  4934.5 1534.77  4963.4 1533.34  4969.1 1532.14  4977.4 1531.81  4977.7 1531.31
  4981.3 1531.31  4981.6 1531.81  5002.4 1532.71  5007.0 1534.94  5023.1 1535.70
  5059.9 1535.14  5082.7 1534.15  5126.4 1534.89  5148.2 1535.87  5153.9 1537.07
  5175.7 1538.60  5229.7 1540.88  5235.4 1541.67  5294.2 1542.51  5367.7 1543.91
#Mann=6,-1,0
  4354.5   0.035       0  4355.2   0.045       0  4626.4    0.07       0
  4977.4    0.07       0  4981.6    0.07       0  5294.2   0.045       0
Bank Sta=4977.4,4981.6
Exp/Cntr=0.3,0.1

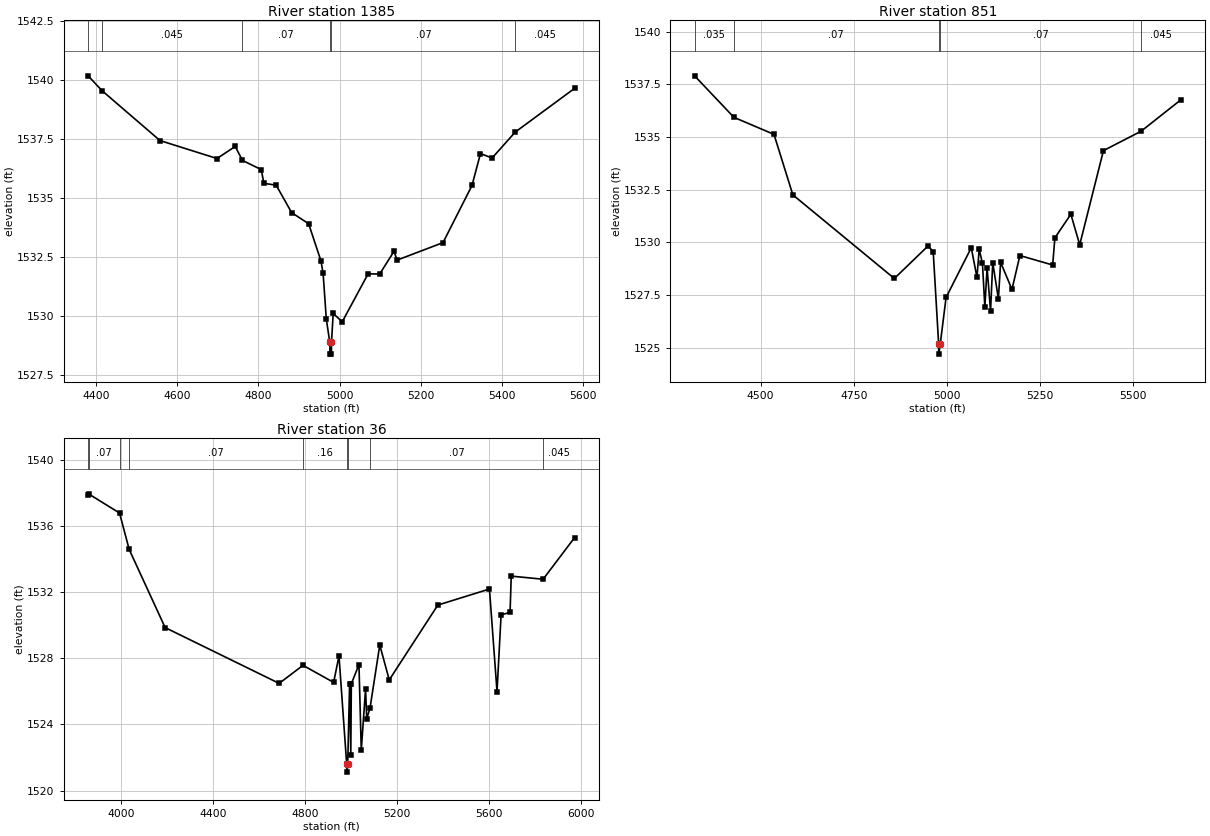
Type RM Length L Ch R = 1,1385,534,534,534
BEGIN DESCRIPTION:
Mapping XS 01b9b381
END DESCRIPTION:
XS GIS Cut Line= 3
      1612432.92      6973057.05      1612214.82      6972477.53
      1611773.63      6972102.58
#Sta/Elev= 30
  4380.8 1540.16  4415.2 1539.53  4557.8 1537.42  4698.2 1536.66  4743.1 1537.17
  4760.9 1536.58  4807.2 1536.19  4813.7 1535.61  4844.0 1535.53  4882.0 1534.37
  4923.9 1533.90  4954.2 1532.33  4959.5 1531.81  4967.4 1529.87  4976.0 1528.88
  4976.3 1528.38  4980.0 1528.38  4980.2 1528.88  4984.4 1530.10  5006.7 1529.75
  5070.4 1531.78  5098.9 1531.77  5134.1 1532.73  5141.8 1532.36  5254.9 1533.10
  5326.3 1535.52  5347.1 1536.87  5375.7 1536.68  5432.8 1537.78  5579.0 1539.63
#Mann=6,-1,0
  4380.8   0.035       0  4415.2   0.045       0  4760.9    0.07       0
  4976.0    0.07       0  4980.2    0.07       0  5432.8   0.045       0
Bank Sta=4976,4980.2
Exp/Cntr=0.3,0.1

Type RM Length L Ch R = 1,851,815,815,815
BEGIN DESCRIPTION:
Mapping XS 3161ee9a
END DESCRIPTION:
XS GIS Cut Line= 3
      1612526.23      6973059.27      1612615.07      6972387.83
      1612085.71      6972050.13
#Sta/Elev= 30
  4322.7 1537.90  4428.2 1535.93  4535.8 1535.12  4586.3 1532.25  4858.6 1528.28
  4949.4 1529.83  4962.9 1529.55  4977.4 1525.19  4977.7 1524.69  4981.9 1525.19
  4997.4 1527.38  5065.0 1529.74  5080.3 1528.33  5086.2 1529.67  5095.0 1529.00
  5101.4 1526.92  5107.4 1528.79  5116.7 1526.74  5122.6 1529.03  5137.8 1527.31
  5143.7 1529.05  5174.2 1527.76  5195.4 1529.37  5283.4 1528.92  5289.3 1530.21
  5332.2 1531.33  5355.9 1529.88  5419.6 1534.35  5520.6 1535.27  5627.9 1536.77
#Mann=5,-1,0
  4322.7   0.035       0  4428.2    0.07       0  4977.4    0.07       0
  4981.9    0.07       0  5520.6   0.045       0
Bank Sta=4977.4,4981.9
Exp/Cntr=0.3,0.1

Type RM Length L Ch R = 1,36,0,0,0
BEGIN DESCRIPTION:
Chimney Creek 1124 1.0
END DESCRIPTION:
XS GIS Cut Line= 3
      1612710.70      6973254.56      1613180.00      6972213.78
      1612219.51      6972058.90
#Sta/Elev= 30
  3858.3 1537.88  3860.1 1537.93  3994.9 1536.77  4036.8 1534.57  4193.1 1529.85
  4688.7 1526.48  4792.2 1527.57  4925.5 1526.54  4948.7 1528.14  4982.1 1521.62
  4982.4 1521.12  4986.6 1521.62  4994.9 1526.46  5000.0 1522.18  5002.4 1526.46
  5035.5 1527.61  5045.6 1522.45  5064.2 1526.14  5069.3 1524.34  5083.7 1525.00
  5126.0 1528.80  5167.1 1526.69  5378.3 1531.21  5602.7 1532.18  5635.6 1525.98
  5653.3 1530.62  5692.3 1530.77  5697.4 1532.96  5835.9 1532.77  5972.9 1535.29
#Mann=9,-1,0
  3858.3   0.045       0  3860.1    0.07       0  3994.9   0.045       0
  4036.8    0.07       0  4792.2    0.16       0  4982.1    0.07       0
  4986.6    0.16       0  5083.7    0.07       0  5835.9   0.045       0
Bank Sta=4982.1,4986.6
Exp/Cntr=0.3,0.1

Chan Stop Cuts=-1