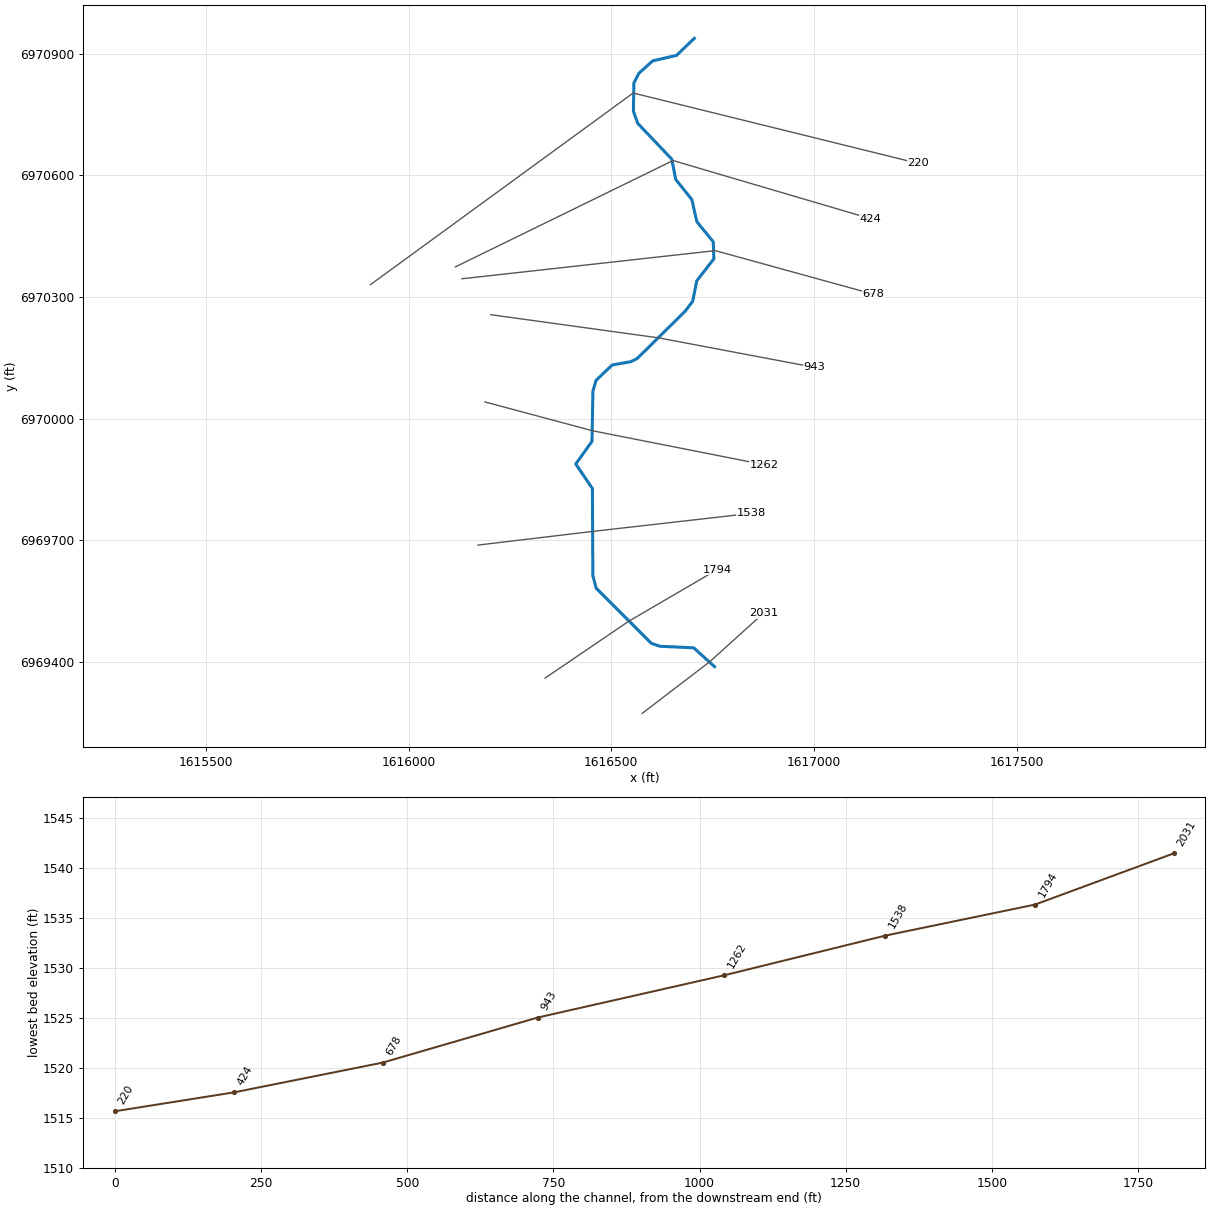
--- Chimney Creek 1125.prj (project) ---

Proj Title=Chimney Creek 1125 Base Level Engineering
Current Plan=p01
Default Exp/Contr=0.3,0.1
English Units
Geom File=g01
Flow File=f01
Plan File=p01
BEGIN DESCRIPTION:
Chimney Creek 1125
END DESCRIPTION:

--- Chimney Creek 1125.p01 (plan) ---

Plan Title=Multiple Run
Short Identifier=Multiple
Geom File=g01
Flow File=f01
Subcritical Flow
K Sum by GR= 0
Std Step Tol= 0.01
Critical Tol= 0.01
Num of Std Step Trials= 20
Max Error Tol= 0.3
Flow Tol Ratio= 0.001
Split Flow NTrial= 30
Split Flow Tol= 0.02
Split Flow Ratio= 0.02
Log Output Level= 0
Friction Slope Method= 1
Unsteady Friction Slope Method= 2
Unsteady Bridges Friction Slope Method= 1
Parabolic Critical Depth
Global Vel Dist=  1 , 1 , 1
Global Log Level= 0
CheckData=True
Encroach Param= -1, 0, 0, 0
BEGIN DESCRIPTION:
Multiple Run
END DESCRIPTION:

--- Chimney Creek 1125.f01 (steady flow) ---

Flow Title=Multiple
Number of Profiles=7
Profile Names=10-year,25-year,50-year,1pct_min,100-year,1pct_plu,500-year
River Rch & RM= Chimney Creek 11,Reach-1,2031
     225     309     378     230     459     916     686
Boundary for River Rch & Prof#=Chimney Creek 11,Reach-1,1
Up Type=0
Dn Type=3
Dn Slope=0.005
Boundary for River Rch & Prof#=Chimney Creek 11,Reach-1,2
Up Type=0
Dn Type=3
Dn Slope=0.005
Boundary for River Rch & Prof#=Chimney Creek 11,Reach-1,3
Up Type=0
Dn Type=3
Dn Slope=0.005
Boundary for River Rch & Prof#=Chimney Creek 11,Reach-1,4
Up Type=0
Dn Type=3
Dn Slope=0.005
Boundary for River Rch & Prof#=Chimney Creek 11,Reach-1,5
Up Type=0
Dn Type=3
Dn Slope=0.005
Boundary for River Rch & Prof#=Chimney Creek 11,Reach-1,6
Up Type=0
Dn Type=3
Dn Slope=0.005
Boundary for River Rch & Prof#=Chimney Creek 11,Reach-1,7
Up Type=0
Dn Type=3
Dn Slope=0.005

--- Chimney Creek 1125.g01 (geometry) ---

Geom Title=Existing Conditions

River Reach=Chimney Creek 11,Reach-1
Reach XY= 30
      1616755.00      6969388.00      1616703.59      6969434.61
      1616620.19      6969438.47      1616598.82      6969445.84
      1616462.81      6969581.81      1616454.70      6969612.88
      1616453.62      6969827.56      1616412.56      6969888.00
      1616452.53      6969943.86      1616454.93      6970068.11
      1616462.70      6970094.47      1616502.43      6970132.26
      1616548.91      6970140.55      1616564.66      6970148.79
      1616681.99      6970264.53      1616701.06      6970289.63
      1616711.18      6970340.19      1616753.21      6970394.11
      1616751.66      6970436.28      1616711.16      6970485.80
      1616698.92      6970540.20      1616659.19      6970589.74
      1616649.15      6970640.29      1616565.45      6970728.22
      1616554.78      6970758.06      1616555.86      6970827.67
      1616568.17      6970851.66      1616602.34      6970882.41
      1616661.11      6970895.95      1616705.00      6970938.00

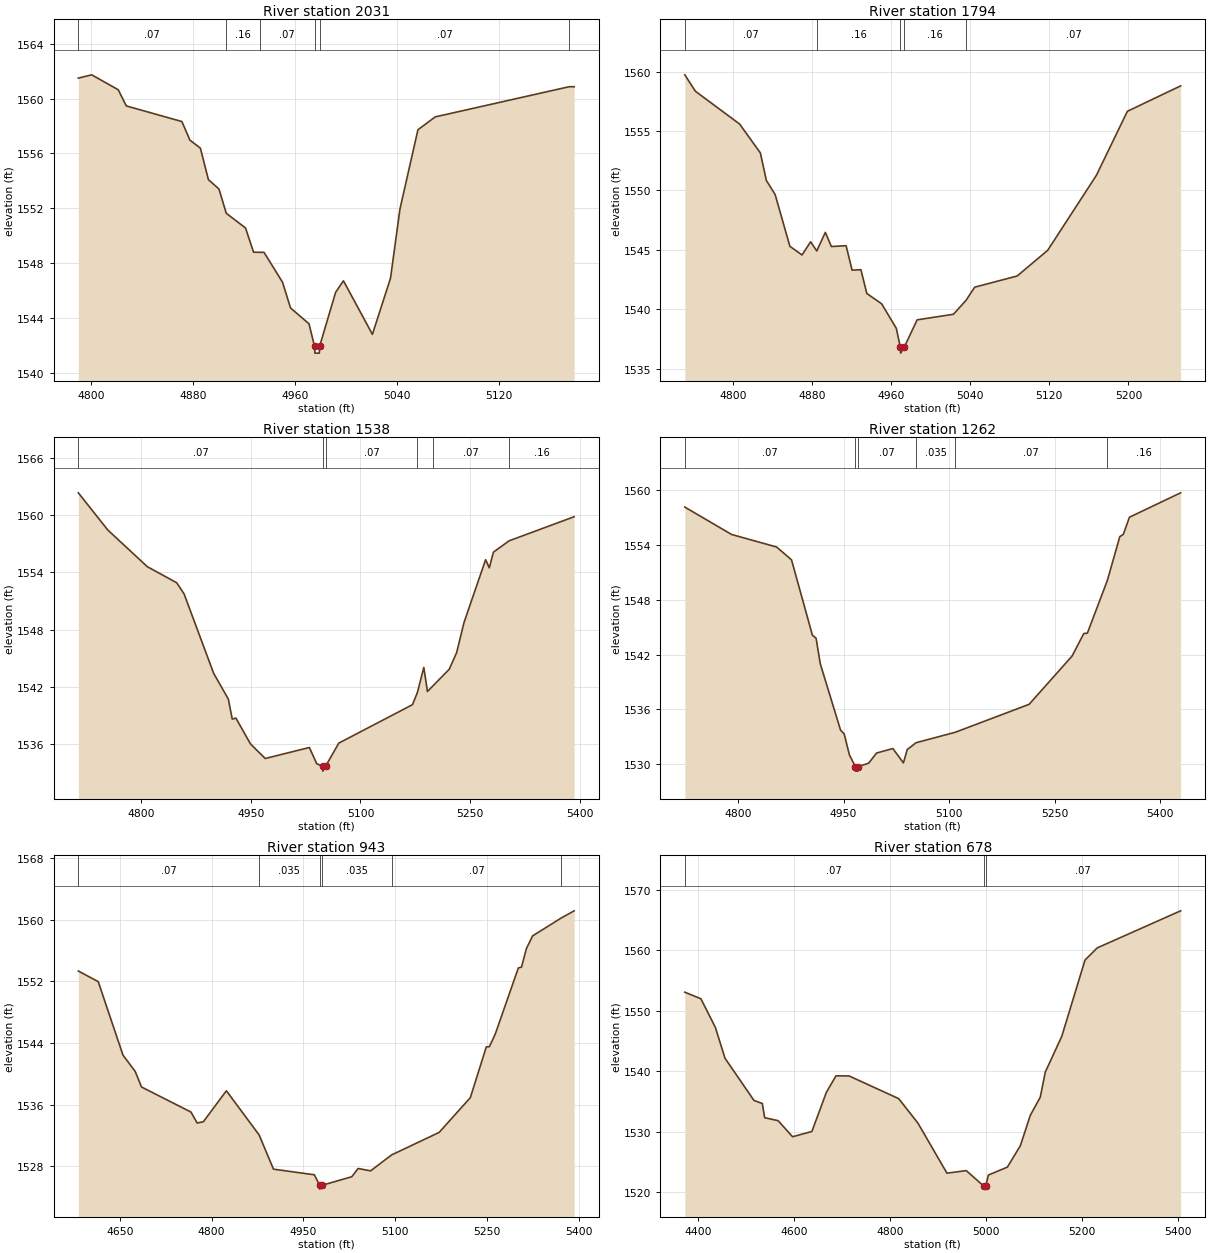
Type RM Length L Ch R = 1,2031,237,237,237
BEGIN DESCRIPTION:
Chimney Creek 1125 4.0
END DESCRIPTION:
XS GIS Cut Line= 3
      1616576.44      6969272.95      1616743.18      6969400.46
      1616875.94      6969520.36
#Sta/Elev= 30
  4790.1 1561.50  4800.6 1561.74  4821.4 1560.65  4827.7 1559.47  4871.3 1558.33
  4877.6 1556.97  4885.8 1556.39  4892.1 1554.09  4900.4 1553.40  4906.1 1551.63
  4921.2 1550.56  4927.5 1548.79  4932.6 1548.78  4935.7 1548.78  4950.2 1546.60
  4956.5 1544.72  4971.0 1543.56  4975.3 1541.92  4975.6 1541.42  4979.1 1541.42
  4979.3 1541.92  4991.9 1545.87  4998.0 1546.70  5020.7 1542.79  5034.9 1546.89
  5042.3 1551.94  5056.4 1557.73  5070.0 1558.67  5174.9 1560.87  5178.9 1560.87
#Mann=6,-1,0
  4790.1    0.07       0  4906.1    0.16       0  4932.6    0.07       0
  4975.3    0.07       0  4979.3    0.07       0  5174.9   0.035       0
Bank Sta=4975.3,4979.3
Exp/Cntr=0.3,0.1

Type RM Length L Ch R = 1,1794,256,256,256
BEGIN DESCRIPTION:
Mapping XS f03053da
END DESCRIPTION:
XS GIS Cut Line= 3
      1616336.79      6969359.94      1616543.80      6969500.55
      1616761.26      6969627.40
#Sta/Elev= 30
  4750.9 1559.73  4761.6 1558.35  4806.4 1555.59  4827.4 1553.16  4833.5 1550.84
  4842.4 1549.65  4857.3 1545.30  4869.6 1544.57  4878.3 1545.68  4884.5 1544.91
  4893.2 1546.47  4899.3 1545.28  4914.2 1545.35  4920.3 1543.29  4929.2 1543.33
  4935.2 1541.33  4950.2 1540.46  4965.1 1538.39  4969.1 1536.81  4969.4 1536.31
  4973.1 1536.81  4986.1 1539.11  5022.9 1539.58  5035.8 1540.77  5044.4 1541.86
  5087.4 1542.80  5118.3 1544.96  5167.6 1551.27  5199.0 1556.66  5252.9 1558.80
#Mann=5,-1,0
  4750.9    0.07       0  4884.5    0.16       0  4969.1    0.07       0
  4973.1    0.16       0  5035.8    0.07       0
Bank Sta=4969.1,4973.1
Exp/Cntr=0.3,0.1

Type RM Length L Ch R = 1,1538,276,276,276
BEGIN DESCRIPTION:
Mapping XS 2141313c
END DESCRIPTION:
XS GIS Cut Line= 3
      1616171.43      6969688.05      1616455.26      6969721.90
      1616844.61      6969766.18
#Sta/Elev= 30
  4714.4 1562.32  4754.7 1558.43  4808.6 1554.60  4848.9 1552.91  4859.0 1551.74
  4899.3 1543.45  4919.4 1540.75  4924.8 1538.65  4929.8 1538.76  4949.6 1536.07
  4969.8 1534.53  5030.2 1535.68  5040.2 1533.99  5048.3 1533.71  5048.5 1533.21
  5052.3 1533.71  5070.4 1536.14  5171.1 1540.16  5177.8 1541.42  5186.6 1544.06
  5191.6 1541.54  5199.0 1542.12  5221.4 1543.87  5231.5 1545.61  5241.5 1548.74
  5271.1 1555.33  5276.1 1554.47  5281.8 1556.12  5303.2 1557.30  5392.1 1559.82
#Mann=6,-1,0
  4714.4    0.07       0  5048.3    0.07       0  5052.3    0.07       0
  5177.8   0.035       0  5199.0    0.07       0  5303.2    0.16       0
Bank Sta=5048.3,5052.3
Exp/Cntr=0.3,0.1

Type RM Length L Ch R = 1,1262,319,319,319
BEGIN DESCRIPTION:
Mapping XS 36ffbbde
END DESCRIPTION:
XS GIS Cut Line= 3
      1616188.86      6970041.10      1616454.52      6969969.91
      1616876.43      6969886.57
#Sta/Elev= 30
  4724.2 1558.14  4790.8 1555.14  4854.8 1553.77  4876.0 1552.36  4905.7 1544.11
  4910.9 1543.79  4916.9 1540.98  4945.7 1533.73  4950.9 1533.31  4958.3 1531.01
  4966.7 1529.74  4966.9 1529.24  4970.4 1529.24  4970.7 1529.74  4985.7 1530.11
  4996.9 1531.22  5020.1 1531.71  5035.1 1530.14  5040.5 1531.60  5053.1 1532.35
  5108.7 1533.49  5213.8 1536.55  5274.9 1541.83  5291.6 1544.30  5296.7 1544.34
  5325.1 1550.11  5342.8 1554.90  5347.9 1555.17  5356.5 1557.03  5429.3 1559.70
#Mann=6,-1,0
  4724.2    0.07       0  4966.7    0.07       0  4970.7    0.07       0
  5053.1   0.035       0  5108.7    0.07       0  5325.1    0.16       0
Bank Sta=4966.7,4970.7
Exp/Cntr=0.3,0.1

Type RM Length L Ch R = 1,943,265,265,265
BEGIN DESCRIPTION:
Mapping XS a1780cb0
END DESCRIPTION:
XS GIS Cut Line= 3
      1616202.82      6970256.36      1616617.71      6970199.07
      1617001.57      6970126.45
#Sta/Elev= 30
  4582.4 1553.32  4614.9 1551.94  4655.3 1542.41  4675.2 1540.30  4685.6 1538.27
  4766.3 1535.02  4776.4 1533.60  4786.5 1533.76  4824.1 1537.78  4877.6 1532.05
  4901.0 1527.61  4967.8 1526.88  4976.3 1525.52  4976.6 1525.02  4980.3 1525.52
  5028.9 1526.63  5039.2 1527.70  5059.5 1527.39  5093.9 1529.46  5171.5 1532.38
  5222.4 1536.89  5248.5 1543.48  5253.5 1543.50  5263.1 1545.14  5300.8 1553.72
  5305.9 1553.83  5314.0 1556.24  5324.1 1557.88  5371.0 1560.21  5391.9 1561.13
#Mann=6,-1,0
  4582.4    0.07       0  4877.6   0.035       0  4976.3   0.035       0
  4980.3   0.035       0  5093.9    0.07       0  5371.0    0.16       0
Bank Sta=4976.3,4980.3
Exp/Cntr=0.3,0.1

Type RM Length L Ch R = 1,678,254,254,254
BEGIN DESCRIPTION:
Mapping XS 779f4157
END DESCRIPTION:
XS GIS Cut Line= 3
      1616131.63      6970344.91      1616756.60      6970414.35
      1617147.23      6970306.71
#Sta/Elev= 30
  4372.4 1553.08  4406.0 1551.99  4436.2 1547.25  4456.3 1542.15  4516.7 1535.18
  4534.0 1534.68  4539.0 1532.33  4567.0 1531.84  4597.1 1529.18  4637.4 1530.05
  4667.6 1536.51  4687.7 1539.25  4715.1 1539.23  4818.5 1535.48  4858.7 1531.42
  4919.1 1523.16  4959.4 1523.58  4995.9 1521.02  4996.1 1520.52  4999.9 1521.02
  5005.5 1522.85  5045.1 1524.16  5072.2 1527.70  5092.9 1532.72  5113.7 1535.72
  5124.2 1539.87  5158.6 1545.79  5207.0 1558.39  5232.5 1560.40  5406.4 1566.53
#Mann=3,-1,0
  4372.4    0.07       0  4995.9    0.07       0  4999.9    0.07       0
Bank Sta=4995.9,4999.9
Exp/Cntr=0.3,0.1

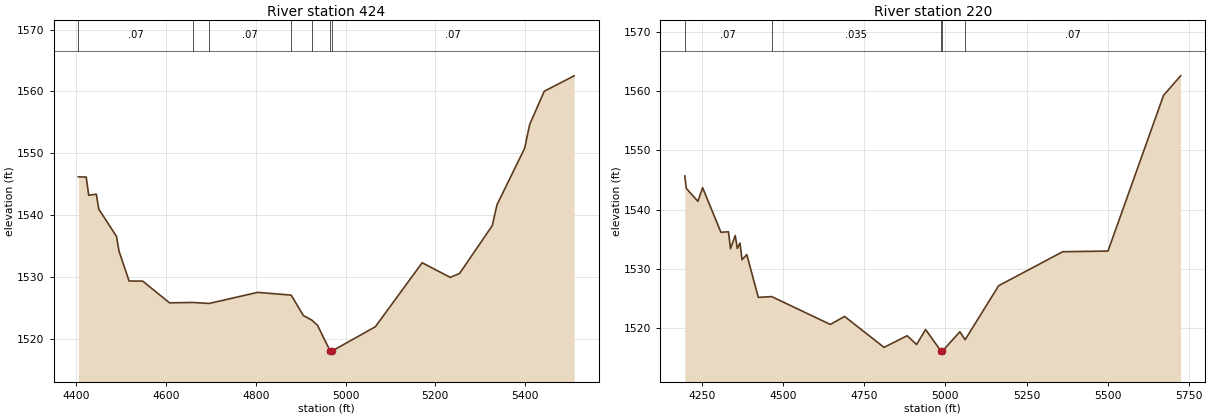
Type RM Length L Ch R = 1,424,204,204,204
BEGIN DESCRIPTION:
Mapping XS 52dffea1
END DESCRIPTION:
XS GIS Cut Line= 3
      1616115.96      6970374.41      1616652.44      6970636.57
      1617140.15      6970493.03
#Sta/Elev= 30
  4404.3 1546.21  4421.9 1546.16  4427.5 1543.23  4444.4 1543.40  4450.0 1540.98
  4489.4 1536.58  4495.0 1534.20  4517.5 1529.37  4547.9 1529.35  4607.6 1525.84
  4659.3 1525.90  4696.0 1525.74  4803.9 1527.53  4878.9 1527.09  4905.9 1523.80
  4925.0 1523.04  4937.5 1522.22  4965.9 1518.05  4966.1 1517.55  4969.9 1518.05
  5066.6 1521.98  5170.9 1532.32  5233.4 1529.96  5254.3 1530.58  5327.2 1538.32
  5337.8 1541.70  5399.3 1550.80  5410.6 1554.66  5443.1 1560.04  5509.8 1562.53
#Mann=7,-1,0
  4404.3    0.07       0  4659.3   0.035       0  4696.0    0.07       0
  4878.9   0.035       0  4925.0    0.07       0  4965.9    0.07       0
  4969.9    0.07       0
Bank Sta=4965.9,4969.9
Exp/Cntr=0.3,0.1

Type RM Length L Ch R = 1,220,0,0,0
BEGIN DESCRIPTION:
Chimney Creek 1125 1.0
END DESCRIPTION:
XS GIS Cut Line= 3
      1615906.01      6970330.33      1616554.19      6970803.14
      1617257.47      6970629.50
#Sta/Elev= 30
  4197.7 1545.67  4202.4 1543.58  4238.0 1541.40  4252.6 1543.69  4309.0 1536.18
  4332.2 1536.28  4338.4 1533.42  4353.1 1535.65  4359.3 1533.47  4367.7 1534.37
  4373.9 1531.56  4388.6 1532.43  4424.1 1525.22  4465.4 1525.35  4645.8 1520.66
  4689.8 1522.01  4811.1 1516.80  4882.2 1518.76  4911.5 1517.28  4939.1 1519.80
  4986.8 1516.16  4987.1 1515.66  4990.8 1516.16  5044.7 1519.43  5060.9 1518.09
  5164.0 1527.18  5361.3 1532.91  5500.8 1533.02  5671.8 1559.25  5724.4 1562.54
#Mann=5,-1,0
  4197.7    0.07       0  4465.4   0.035       0  4986.8   0.035       0
  4990.8   0.035       0  5060.9    0.07       0
Bank Sta=4986.8,4990.8
Exp/Cntr=0.3,0.1

Chan Stop Cuts=-1