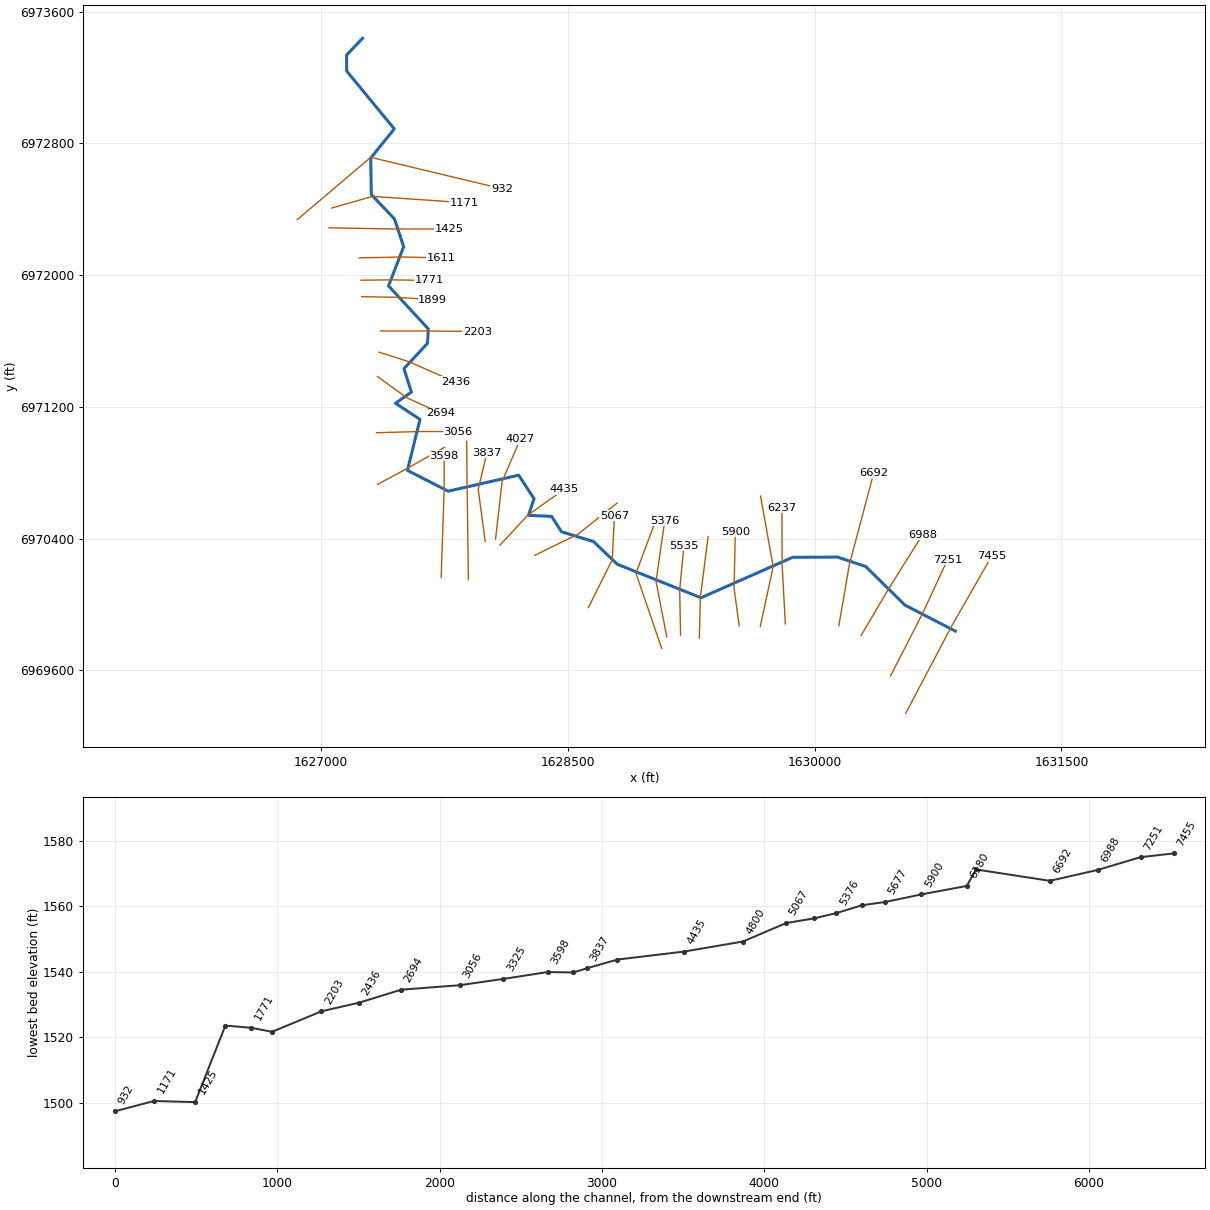
--- Chimney Creek 1126.prj (project) ---

Proj Title=Chimney Creek 1126 Base Level Engineering
Current Plan=p01
Default Exp/Contr=0.3,0.1
English Units
Geom File=g01
Flow File=f01
Plan File=p01
BEGIN DESCRIPTION:
Chimney Creek 1126
END DESCRIPTION:

--- Chimney Creek 1126.p01 (plan) ---

Plan Title=Multiple Run
Short Identifier=Multiple
Geom File=g01
Flow File=f01
Subcritical Flow
K Sum by GR= 0
Std Step Tol= 0.01
Critical Tol= 0.01
Num of Std Step Trials= 20
Max Error Tol= 0.3
Flow Tol Ratio= 0.001
Split Flow NTrial= 30
Split Flow Tol= 0.02
Split Flow Ratio= 0.02
Log Output Level= 0
Friction Slope Method= 1
Unsteady Friction Slope Method= 2
Unsteady Bridges Friction Slope Method= 1
Parabolic Critical Depth
Global Vel Dist=  1 , 1 , 1
Global Log Level= 0
CheckData=True
Encroach Param= -1, 0, 0, 0
BEGIN DESCRIPTION:
Multiple Run
END DESCRIPTION:

--- Chimney Creek 1126.f01 (steady flow) ---

Flow Title=Multiple
Number of Profiles=7
Profile Names=10-year,25-year,50-year,1pct_min,100-year,1pct_plu,500-year
River Rch & RM= Chimney Creek 11,Reach-1,7455
     237     327     400     245     488     974     734
River Rch & RM= Chimney Creek 11,Reach-1,7251
     329     462     573     354     705    1408    1084
Boundary for River Rch & Prof#=Chimney Creek 11,Reach-1,1
Up Type=0
Dn Type=3
Dn Slope=0.005
Boundary for River Rch & Prof#=Chimney Creek 11,Reach-1,2
Up Type=0
Dn Type=3
Dn Slope=0.005
Boundary for River Rch & Prof#=Chimney Creek 11,Reach-1,3
Up Type=0
Dn Type=3
Dn Slope=0.005
Boundary for River Rch & Prof#=Chimney Creek 11,Reach-1,4
Up Type=0
Dn Type=3
Dn Slope=0.005
Boundary for River Rch & Prof#=Chimney Creek 11,Reach-1,5
Up Type=0
Dn Type=3
Dn Slope=0.005
Boundary for River Rch & Prof#=Chimney Creek 11,Reach-1,6
Up Type=0
Dn Type=3
Dn Slope=0.005
Boundary for River Rch & Prof#=Chimney Creek 11,Reach-1,7
Up Type=0
Dn Type=3
Dn Slope=0.005

--- Chimney Creek 1126.g01 (geometry) ---

Geom Title=Existing Conditions

River Reach=Chimney Creek 11,Reach-1
Reach XY= 30
      1630855.00      6969838.00      1630548.94      6969996.14
      1630311.17      6970230.14      1630139.78      6970287.48
      1629866.97      6970286.04      1629310.57      6970040.28
      1628802.70      6970243.83      1628657.30      6970382.17
      1628463.35      6970441.19      1628403.72      6970534.51
      1628262.57      6970541.08      1628296.92      6970641.28
      1628203.57      6970784.93      1627775.18      6970687.71
      1627527.55      6970814.16      1627604.24      6971123.56
      1627455.16      6971221.89      1627551.92      6971289.43
      1627506.62      6971431.96      1627649.60      6971585.57
      1627654.76      6971672.78      1627413.00      6971934.66
      1627504.62      6972172.73      1627449.48      6972340.43
      1627308.54      6972489.46      1627304.63      6972710.88
      1627447.93      6972888.00      1627158.47      6973239.50
      1627158.40      6973336.52      1627255.00      6973438.00

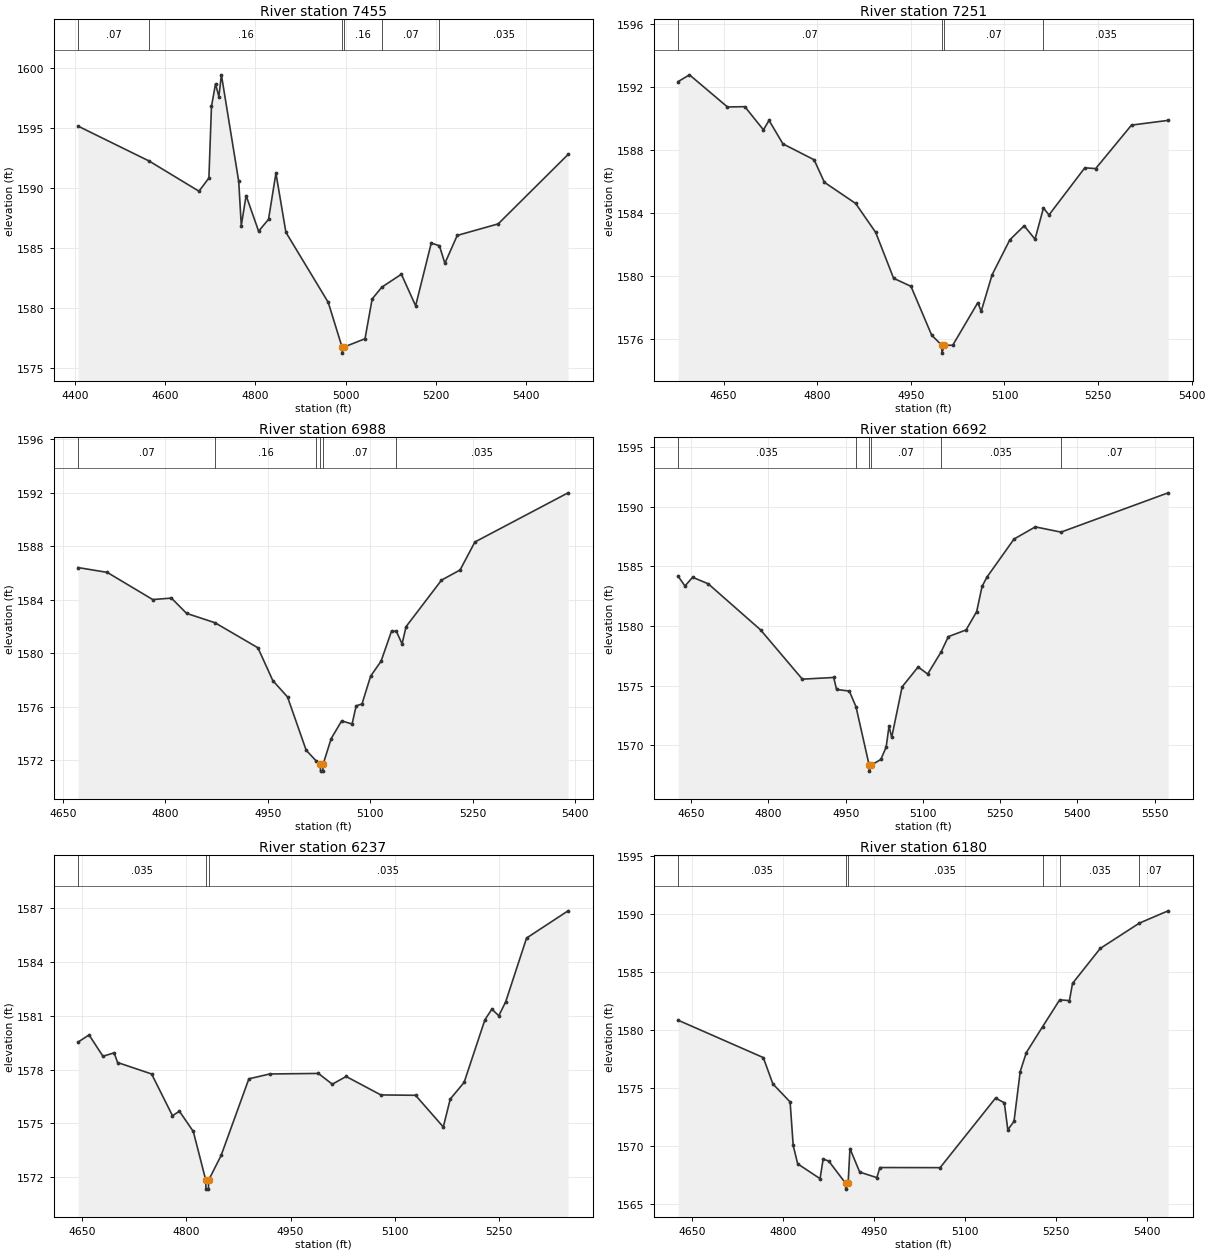
Type RM Length L Ch R = 1,7455,204,204,204
BEGIN DESCRIPTION:
Chimney Creek 1126 15.0
END DESCRIPTION:
XS GIS Cut Line= 3
      1630553.80      6969338.27      1630830.00      6969863.00
      1631074.63      6970291.39
#Sta/Elev= 30
  4406.9 1595.14  4564.7 1592.23  4675.0 1589.72  4697.0 1590.82  4702.7 1596.78
  4711.7 1598.66  4719.1 1597.59  4724.7 1599.41  4763.1 1590.54  4768.8 1586.86
  4779.5 1589.36  4807.2 1586.39  4829.2 1587.38  4845.6 1591.22  4867.7 1586.30
  4961.5 1580.47  4992.2 1576.74  4992.5 1576.24  4996.2 1576.74  5043.1 1577.44
  5058.9 1580.75  5080.3 1581.73  5123.7 1582.81  5155.3 1580.18  5189.9 1585.40
  5208.0 1585.18  5220.2 1583.72  5247.5 1586.04  5338.3 1587.00  5493.2 1592.78
#Mann=6,-1,0
  4406.9    0.07       0  4564.7    0.16       0  4992.2    0.07       0
  4996.2    0.16       0  5080.3    0.07       0  5208.0   0.035       0
Bank Sta=4992.2,4996.2
Exp/Cntr=0.3,0.1

Type RM Length L Ch R = 1,7251,263,263,263
BEGIN DESCRIPTION:
Mapping XS a573fd10
END DESCRIPTION:
XS GIS Cut Line= 3
      1630461.91      6969566.37      1630656.36      6969944.86
      1630807.42      6970271.28
#Sta/Elev= 30
  4577.1 1592.32  4595.3 1592.75  4656.2 1590.71  4684.0 1590.73  4713.8 1589.26
  4722.8 1589.86  4745.0 1588.37  4795.0 1587.36  4811.5 1585.93  4861.5 1584.59
  4893.7 1582.75  4922.4 1579.84  4950.2 1579.33  4983.4 1576.23  4999.6 1575.59
  4999.8 1575.09  5003.6 1575.59  5017.1 1575.59  5057.3 1578.29  5062.8 1577.75
  5080.2 1580.06  5108.6 1582.28  5131.6 1583.17  5149.0 1582.32  5162.5 1584.30
  5171.4 1583.86  5228.8 1586.85  5246.2 1586.80  5303.6 1589.56  5362.3 1589.86
#Mann=4,-1,0
  4577.1    0.07       0  4999.6    0.07       0  5003.6    0.07       0
  5162.5   0.035       0
Bank Sta=4999.6,5003.6
Exp/Cntr=0.3,0.1

Type RM Length L Ch R = 1,6988,296,296,296
BEGIN DESCRIPTION:
Mapping XS 10e4e8fa
END DESCRIPTION:
XS GIS Cut Line= 3
      1630283.11      6969811.20      1630449.76      6970094.16
      1630656.04      6970423.51
#Sta/Elev= 30
  4672.3 1586.40  4715.0 1586.04  4781.6 1584.01  4808.9 1584.12  4831.1 1582.98
  4872.7 1582.28  4935.5 1580.41  4957.3 1577.96  4978.8 1576.74  5006.1 1572.76
  5020.6 1571.97  5026.8 1571.70  5027.1 1571.20  5030.6 1571.20  5030.8 1571.70
  5042.7 1573.63  5058.0 1574.95  5073.3 1574.72  5079.2 1576.07  5087.8 1576.22
  5100.4 1578.29  5115.7 1579.41  5131.1 1581.67  5138.1 1581.64  5146.4 1580.70
  5152.3 1581.99  5204.1 1585.46  5231.3 1586.22  5253.0 1588.31  5389.3 1591.98
#Mann=6,-1,0
  4672.3    0.07       0  4872.7    0.16       0  5020.6    0.07       0
  5026.8    0.07       0  5030.8    0.07       0  5138.1   0.035       0
Bank Sta=5026.8,5030.8
Exp/Cntr=0.3,0.1

Type RM Length L Ch R = 1,6692,455,455,455
BEGIN DESCRIPTION:
Mapping XS 6a26bb15
END DESCRIPTION:
XS GIS Cut Line= 3
      1630147.68      6969870.22      1630211.92      6970243.47
      1630359.49      6970797.31
#Sta/Elev= 30
  4624.5 1584.17  4637.8 1583.35  4652.7 1584.08  4683.1 1583.53  4784.6 1579.68
  4865.8 1575.55  4926.7 1575.69  4932.3 1574.69  4957.1 1574.55  4970.1 1573.23
  4995.6 1568.35  4995.9 1567.85  4999.7 1568.35  5018.3 1568.83  5028.6 1569.86
  5034.2 1571.62  5039.4 1570.68  5059.7 1574.91  5090.7 1576.57  5109.3 1575.98
  5135.4 1577.83  5149.4 1579.11  5183.9 1579.67  5204.5 1581.21  5214.9 1583.31
  5224.4 1584.09  5277.0 1587.28  5318.4 1588.30  5368.3 1587.86  5576.4 1591.15
#Mann=6,-1,0
  4624.5   0.035       0  4970.1    0.07       0  4995.6    0.07       0
  4999.7    0.07       0  5135.4   0.035       0  5368.3    0.07       0
Bank Sta=4995.6,4999.7
Exp/Cntr=0.3,0.1

Type RM Length L Ch R = 1,6237,57,57,57
BEGIN DESCRIPTION:
Mapping XS 596807cf
END DESCRIPTION:
XS GIS Cut Line= 3
      1629822.89      6969882.15      1629803.36      6970240.17
      1629802.06      6970587.81
#Sta/Elev= 30
  4643.7 1579.54  4659.6 1579.94  4679.6 1578.75  4695.7 1578.94  4700.7 1578.40
  4749.7 1577.76  4779.8 1575.43  4789.8 1575.68  4809.8 1574.55  4827.8 1571.83
  4828.0 1571.33  4831.6 1571.33  4831.9 1571.83  4849.9 1573.21  4889.9 1577.49
  4920.0 1577.76  4990.1 1577.79  5010.1 1577.19  5030.1 1577.62  5080.1 1576.59
  5130.1 1576.57  5170.1 1574.80  5180.1 1576.36  5200.1 1577.29  5230.1 1580.79
  5240.1 1581.38  5250.1 1581.01  5260.1 1581.80  5290.1 1585.35  5349.9 1586.87
#Mann=3,-1,0
  4643.7   0.035       0  4827.8   0.035       0  4831.9   0.035       0
Bank Sta=4827.8,4831.9
Exp/Cntr=0.3,0.1

Type RM Length L Ch R = 1,6180,280,280,280
BEGIN DESCRIPTION:
Mapping XS 8a5f5e6a
END DESCRIPTION:
XS GIS Cut Line= 3
      1629670.55      6969865.18      1629748.99      6970229.84
      1629672.17      6970658.20
#Sta/Elev= 30
  4627.0 1580.84  4767.5 1577.62  4783.3 1575.35  4811.7 1573.80  4816.8 1570.05
  4824.2 1568.47  4861.1 1567.19  4866.2 1568.88  4875.4 1568.71  4903.3 1566.79
  4903.5 1566.29  4907.4 1566.79  4910.4 1569.78  4926.5 1567.76  4954.7 1567.28
  4959.8 1568.15  5059.1 1568.14  5150.5 1574.13  5165.0 1573.73  5170.8 1571.40
  5181.0 1572.13  5191.2 1576.41  5201.3 1578.05  5228.0 1580.27  5256.3 1582.59
  5272.4 1582.53  5277.5 1584.01  5323.2 1587.02  5387.7 1589.20  5435.2 1590.26
#Mann=6,-1,0
  4627.0   0.035       0  4903.3   0.035       0  4907.4   0.035       0
  5228.0    0.07       0  5256.3   0.035       0  5387.7    0.07       0
Bank Sta=4903.3,4907.4
Exp/Cntr=0.3,0.1

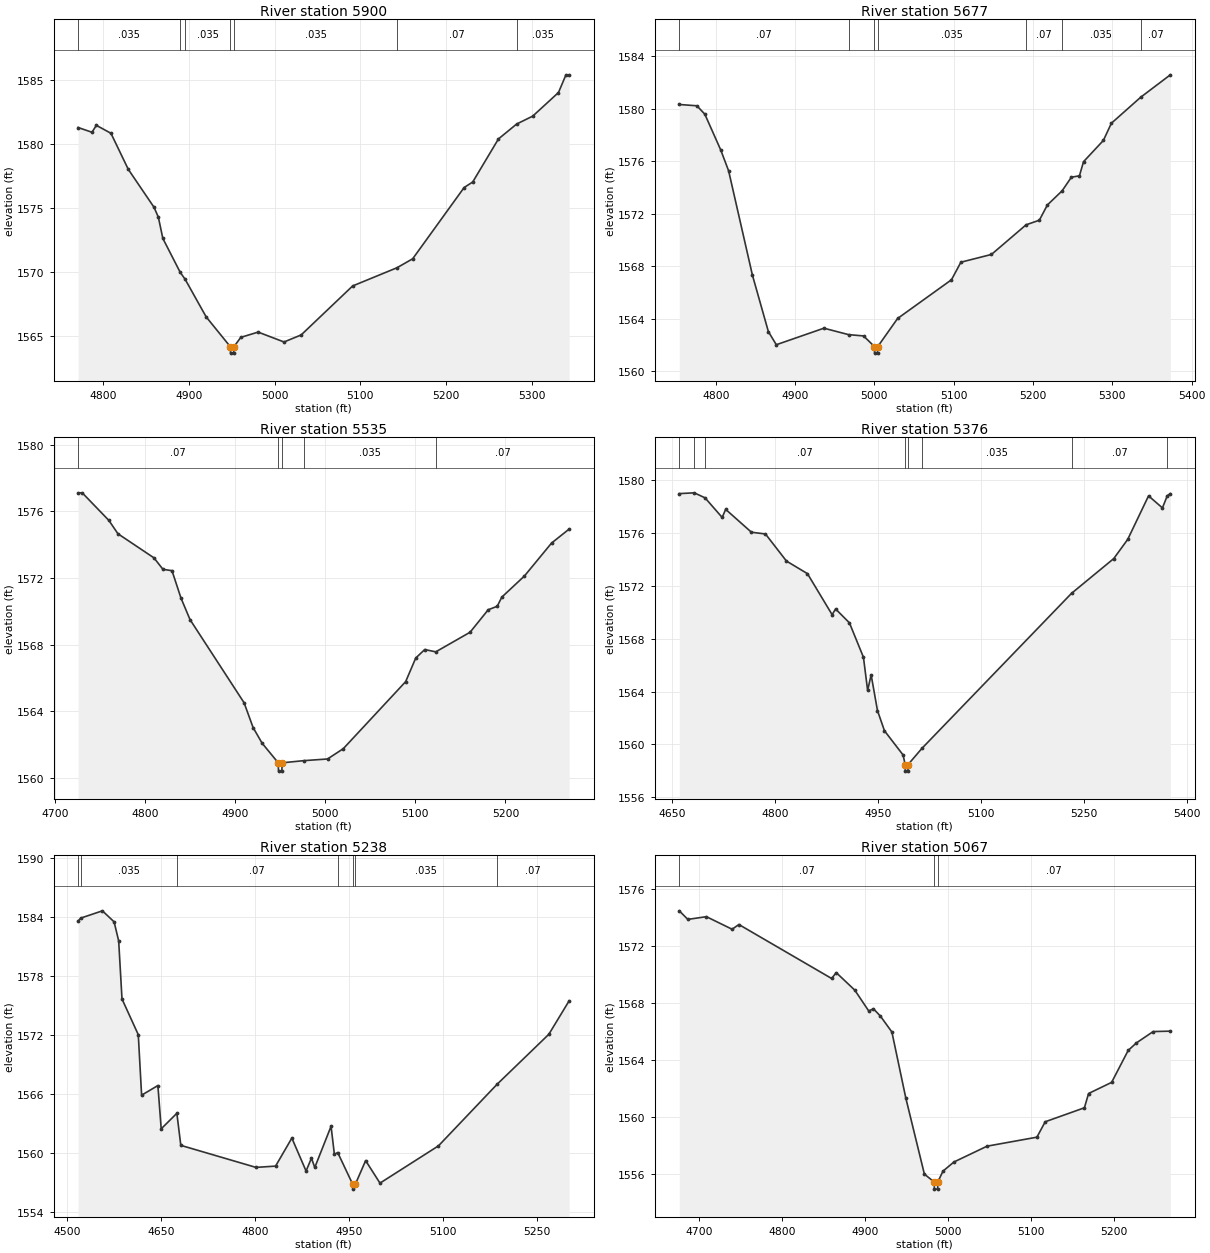
Type RM Length L Ch R = 1,5900,223,223,223
BEGIN DESCRIPTION:
Mapping XS b5648a0c
END DESCRIPTION:
XS GIS Cut Line= 3
      1629542.62      6969870.07      1629511.38      6970099.21
      1629519.19      6970440.36
#Sta/Elev= 30
  4771.0 1581.29  4787.2 1580.92  4792.3 1581.46  4809.3 1580.84  4829.5 1578.03
  4859.6 1575.06  4864.6 1574.29  4869.8 1572.64  4890.0 1570.00  4895.8 1569.45
  4920.3 1566.52  4948.5 1564.19  4948.7 1563.69  4952.4 1563.69  4952.7 1564.19
  4960.7 1564.92  4980.9 1565.33  5011.1 1564.56  5031.1 1565.11  5091.1 1568.93
  5142.8 1570.35  5161.1 1571.05  5221.1 1576.61  5231.1 1577.04  5261.1 1580.40
  5282.3 1581.56  5301.1 1582.18  5331.1 1584.02  5339.8 1585.40  5343.5 1585.40
#Mann=7,-1,0
  4771.0   0.035       0  4890.0    0.07       0  4895.8   0.035       0
  4948.5   0.035       0  4952.7   0.035       0  5142.8    0.07       0
  5282.3   0.035       0
Bank Sta=4948.5,4952.7
Exp/Cntr=0.3,0.1

Type RM Length L Ch R = 1,5677,142,142,142
BEGIN DESCRIPTION:
Mapping XS 461af439
END DESCRIPTION:
XS GIS Cut Line= 3
      1629300.44      6969795.79      1629306.95      6970044.52
      1629353.83      6970411.72
#Sta/Elev= 30
  4754.1 1580.33  4776.3 1580.23  4786.3 1579.59  4806.3 1576.87  4816.3 1575.27
  4846.3 1567.32  4866.4 1563.02  4876.4 1562.02  4936.4 1563.28  4967.5 1562.79
  4986.4 1562.69  5000.1 1561.88  5000.3 1561.38  5004.0 1561.38  5004.3 1561.88
  5029.3 1564.02  5097.2 1566.97  5109.1 1568.31  5147.6 1568.90  5191.3 1571.16
  5208.0 1571.51  5218.1 1572.67  5236.7 1573.75  5248.4 1574.79  5258.5 1574.89
  5263.7 1575.97  5288.7 1577.59  5298.8 1578.90  5335.7 1580.88  5373.1 1582.59
#Mann=7,-1,0
  4754.1    0.07       0  4967.5   0.035       0  5000.1   0.035       0
  5004.3   0.035       0  5191.3    0.07       0  5236.7   0.035       0
  5335.7    0.07       0
Bank Sta=5000.1,5004.3
Exp/Cntr=0.3,0.1

Type RM Length L Ch R = 1,5535,159,159,159
BEGIN DESCRIPTION:
Mapping XS f982f700
END DESCRIPTION:
XS GIS Cut Line= 3
      1629186.63      6969813.83      1629181.21      6970090.53
      1629207.24      6970357.41
#Sta/Elev= 30
  4725.8 1577.12  4730.4 1577.12  4760.0 1575.46  4770.0 1574.66  4810.0 1573.21
  4820.0 1572.52  4830.0 1572.44  4840.0 1570.79  4850.0 1569.50  4910.0 1564.50
  4920.0 1563.01  4930.0 1562.07  4947.9 1560.89  4948.2 1560.39  4951.9 1560.39
  4952.2 1560.89  4976.4 1561.02  5002.6 1561.12  5020.1 1561.74  5089.3 1565.77
  5100.5 1567.19  5110.5 1567.70  5122.7 1567.56  5160.8 1568.74  5180.9 1570.09
  5190.9 1570.30  5196.0 1570.85  5221.1 1572.12  5251.2 1574.10  5270.7 1574.94
#Mann=5,-1,0
  4725.8    0.07       0  4947.9   0.035       0  4952.2    0.07       0
  4976.4   0.035       0  5122.7    0.07       0
Bank Sta=4947.9,4952.2
Exp/Cntr=0.3,0.1

Type RM Length L Ch R = 1,5376,138,138,138
BEGIN DESCRIPTION:
Mapping XS a21956a4
END DESCRIPTION:
XS GIS Cut Line= 3
      1629102.53      6969804.92      1629037.42      6970139.57
      1629090.81      6970509.41
#Sta/Elev= 30
  4660.8 1578.96  4682.6 1579.02  4698.3 1578.64  4723.2 1577.16  4728.3 1577.77
  4765.8 1576.04  4786.2 1575.91  4816.8 1573.86  4847.3 1572.91  4883.2 1569.81
  4888.3 1570.24  4908.4 1569.19  4928.8 1566.59  4934.9 1564.08  4940.0 1565.26
  4949.2 1562.56  4959.4 1561.03  4986.5 1559.20  4989.5 1558.48  4989.8 1557.98
  4993.5 1557.98  4993.8 1558.48  5013.9 1559.70  5231.6 1571.42  5293.1 1574.05
  5313.4 1575.50  5343.7 1578.79  5363.9 1577.88  5371.0 1578.80  5375.4 1578.96
#Mann=8,-1,0
  4660.8    0.07       0  4682.6   0.035       0  4698.3    0.07       0
  4989.5    0.07       0  4993.8    0.07       0  5013.9   0.035       0
  5231.6    0.07       0  5371.0   0.035       0
Bank Sta=4989.5,4993.8
Exp/Cntr=0.3,0.1

Type RM Length L Ch R = 1,5238,171,171,171
BEGIN DESCRIPTION:
Mapping XS edad9b65
END DESCRIPTION:
XS GIS Cut Line= 3
      1629071.61      6969733.57      1628915.68      6970189.65
      1629021.69      6970472.43
#Sta/Elev= 30
  4518.0 1583.60  4522.2 1583.90  4556.8 1584.64  4575.5 1583.52  4582.8 1581.58
  4588.1 1575.68  4614.1 1572.05  4619.4 1565.90  4645.4 1566.88  4650.7 1562.48
  4675.7 1564.06  4682.0 1560.80  4802.0 1558.56  4833.3 1558.69  4859.3 1561.54
  4882.0 1558.19  4890.6 1559.50  4895.9 1558.55  4921.9 1562.74  4927.2 1559.89
  4932.5 1560.07  4956.4 1556.85  4956.6 1556.35  4960.7 1556.85  4977.1 1559.25
  5000.0 1556.96  5093.4 1560.75  5187.0 1567.01  5269.6 1572.09  5302.0 1575.49
#Mann=7,-1,0
  4518.0    0.07       0  4522.2   0.035       0  4675.7    0.07       0
  4932.5   0.035       0  4956.4   0.035       0  4960.7   0.035       0
  5187.0    0.07       0
Bank Sta=4956.4,4960.7
Exp/Cntr=0.3,0.1

Type RM Length L Ch R = 1,5067,267,267,267
BEGIN DESCRIPTION:
Mapping XS c4315db0
END DESCRIPTION:
XS GIS Cut Line= 3
      1628626.76      6969980.98      1628771.51      6970270.96
      1628785.16      6970538.71
#Sta/Elev= 30
  4675.9 1574.44  4686.2 1573.84  4708.6 1574.03  4739.6 1573.15  4747.8 1573.48
  4859.6 1569.70  4865.2 1570.11  4887.6 1568.88  4904.4 1567.42  4910.0 1567.58
  4918.5 1567.06  4932.3 1565.95  4949.1 1561.32  4971.5 1555.99  4983.3 1555.44
  4983.6 1554.94  4987.4 1554.94  4987.7 1555.44  4993.9 1556.20  5007.1 1556.84
  5047.1 1557.95  5107.2 1558.58  5117.2 1559.66  5164.5 1560.64  5169.5 1561.64
  5197.3 1562.42  5217.3 1564.66  5227.3 1565.19  5247.4 1565.98  5268.1 1566.01
#Mann=3,-1,0
  4675.9    0.07       0  4983.3    0.07       0  4987.7    0.07       0
Bank Sta=4983.3,4987.7
Exp/Cntr=0.3,0.1

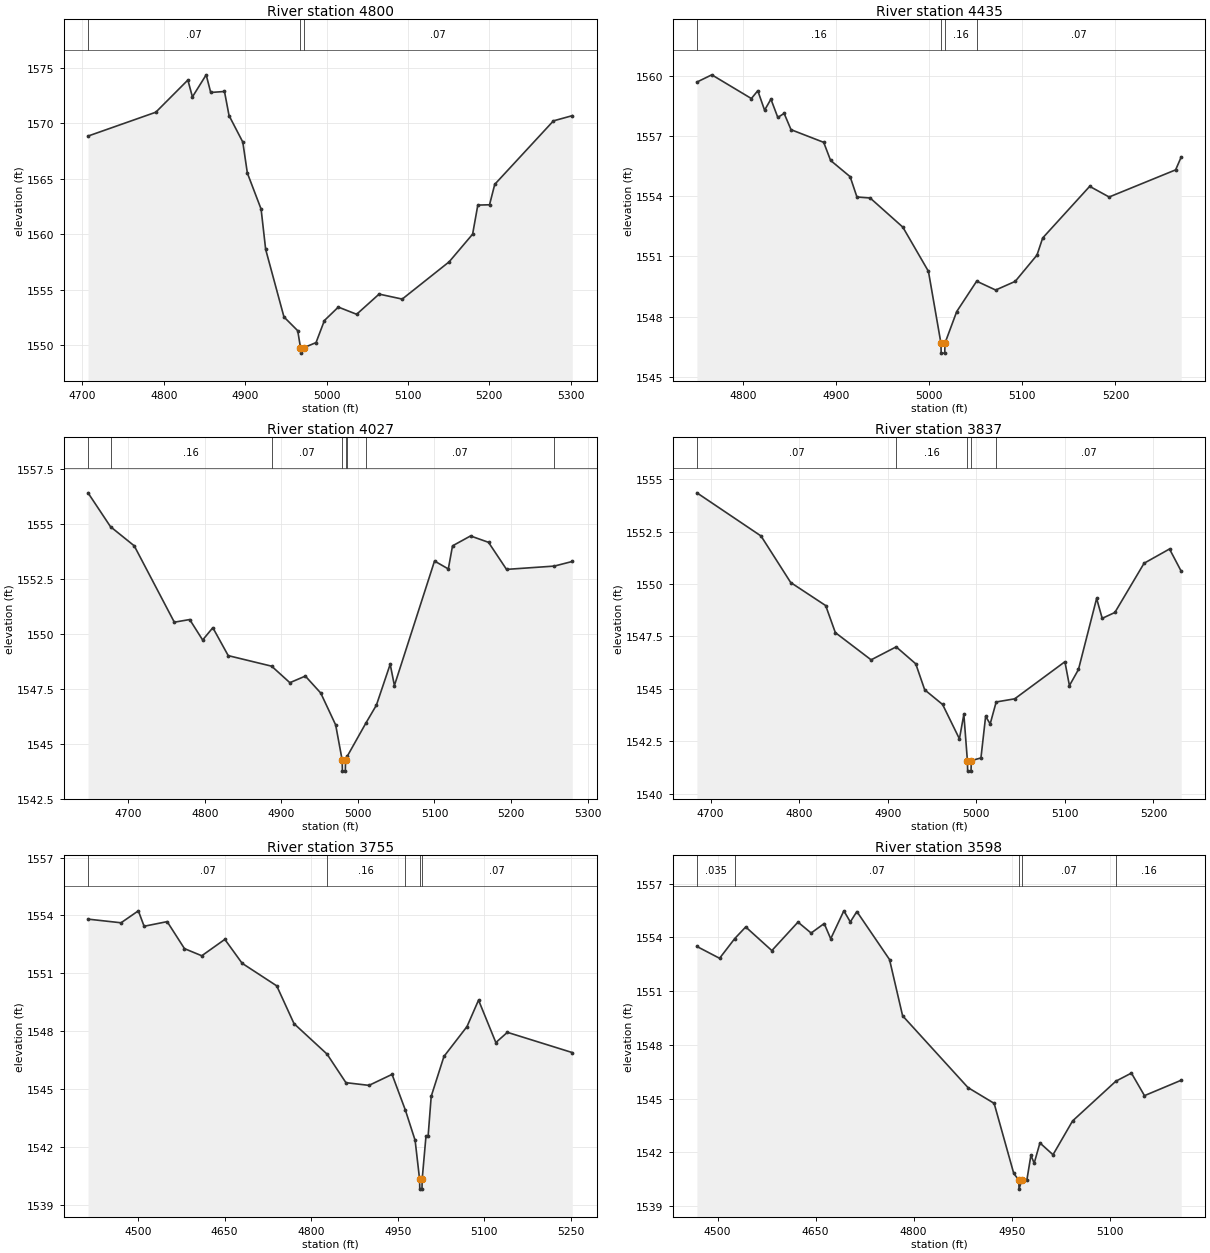
Type RM Length L Ch R = 1,4800,365,365,365
BEGIN DESCRIPTION:
Mapping XS 0ccc7218
END DESCRIPTION:
XS GIS Cut Line= 3
      1628301.27      6970298.26      1628564.33      6970427.19
      1628800.64      6970615.46
#Sta/Elev= 30
  4706.9 1568.83  4790.2 1570.98  4829.6 1573.88  4835.2 1572.36  4852.1 1574.35
  4857.7 1572.76  4874.6 1572.85  4880.2 1570.68  4897.1 1568.29  4902.7 1565.50
  4919.6 1562.25  4925.2 1558.62  4947.7 1552.53  4964.6 1551.29  4968.0 1549.77
  4968.3 1549.27  4972.4 1549.77  4987.1 1550.22  4997.4 1552.21  5014.5 1553.42
  5037.0 1552.77  5064.6 1554.59  5093.0 1554.14  5150.7 1557.50  5179.5 1559.99
  5185.9 1562.61  5200.3 1562.64  5206.7 1564.48  5278.8 1570.20  5302.0 1570.67
#Mann=3,-1,0
  4706.9    0.07       0  4968.0    0.07       0  4972.4    0.07       0
Bank Sta=4968,4972.4
Exp/Cntr=0.3,0.1

Type RM Length L Ch R = 1,4435,408,408,408
BEGIN DESCRIPTION:
Mapping XS d6425951
END DESCRIPTION:
XS GIS Cut Line= 3
      1628089.96      6970360.32      1628259.21      6970542.59
      1628480.85      6970699.35
#Sta/Elev= 30
  4750.5 1559.68  4766.5 1560.04  4809.0 1558.86  4815.9 1559.25  4823.2 1558.28
  4830.0 1558.83  4837.4 1557.92  4844.2 1558.12  4851.6 1557.31  4886.7 1556.68
  4894.1 1555.78  4915.1 1554.97  4922.4 1553.96  4936.6 1553.91  4971.7 1552.46
  4999.2 1550.26  5012.6 1546.69  5012.9 1546.19  5016.7 1546.19  5017.0 1546.69
  5029.6 1548.26  5051.0 1549.77  5071.4 1549.33  5092.4 1549.76  5115.8 1551.07
  5121.9 1551.92  5172.4 1554.49  5193.3 1553.96  5264.7 1555.31  5270.7 1555.95
#Mann=4,-1,0
  4750.5    0.16       0  5012.6    0.07       0  5017.0    0.16       0
  5051.0    0.07       0
Bank Sta=5012.6,5017
Exp/Cntr=0.3,0.1

Type RM Length L Ch R = 1,4027,190,190,190
BEGIN DESCRIPTION:
Mapping XS cee99ba8
END DESCRIPTION:
XS GIS Cut Line= 3
      1628062.81      6970396.07      1628102.96      6970747.66
      1628213.46      6971003.33
#Sta/Elev= 30
  4647.6 1556.41  4677.0 1554.87  4708.0 1554.00  4760.3 1550.53  4780.4 1550.65
  4797.3 1549.72  4810.6 1550.28  4830.7 1549.01  4887.4 1548.53  4911.2 1547.78
  4931.4 1548.08  4951.5 1547.31  4971.0 1545.86  4979.5 1544.26  4979.8 1543.76
  4983.6 1543.76  4983.9 1544.26  4986.2 1544.44  5010.4 1545.94  5024.2 1546.76
  5042.2 1548.62  5047.7 1547.65  5100.1 1553.31  5118.1 1552.95  5123.6 1554.00
  5147.1 1554.45  5170.6 1554.16  5194.1 1552.93  5256.5 1553.08  5280.0 1553.29
#Mann=8,-1,0
  4647.6    0.07       0  4677.0    0.16       0  4887.4    0.07       0
  4979.5    0.07       0  4983.9    0.07       0  4986.2    0.16       0
  5010.4    0.07       0  5256.5   0.035       0
Bank Sta=4979.5,4983.9
Exp/Cntr=0.3,0.1

Type RM Length L Ch R = 1,3837,82,82,82
BEGIN DESCRIPTION:
Mapping XS 09494973
END DESCRIPTION:
XS GIS Cut Line= 3
      1627999.88      6970383.08      1627957.56      6970698.84
      1628010.37      6970920.86
#Sta/Elev= 30
  4684.5 1554.35  4756.9 1552.29  4790.4 1550.07  4829.9 1548.97  4840.8 1547.68
  4881.2 1546.38  4909.5 1547.00  4931.6 1546.19  4941.7 1544.95  4961.9 1544.25
  4980.9 1542.61  4985.9 1543.78  4989.9 1541.57  4990.2 1541.07  4994.0 1541.07
  4994.3 1541.57  5005.2 1541.70  5010.5 1543.69  5015.6 1543.32  5022.4 1544.37
  5043.3 1544.52  5100.0 1546.29  5105.1 1545.15  5115.3 1545.92  5135.8 1549.31
  5142.1 1548.36  5156.4 1548.64  5189.4 1550.99  5218.1 1551.67  5231.3 1550.61
#Mann=5,-1,0
  4684.5    0.07       0  4909.5    0.16       0  4989.9    0.07       0
  4994.3    0.16       0  5022.4    0.07       0
Bank Sta=4989.9,4994.3
Exp/Cntr=0.3,0.1

Type RM Length L Ch R = 1,3755,157,157,157
BEGIN DESCRIPTION:
Mapping XS fbef69c2
END DESCRIPTION:
XS GIS Cut Line= 3
      1627897.90      6970150.74      1627890.09      6970740.54
      1627887.48      6970990.58
#Sta/Elev= 30
  4413.0 1553.81  4470.3 1553.62  4500.3 1554.24  4510.3 1553.44  4550.3 1553.68
  4580.3 1552.28  4610.3 1551.91  4650.3 1552.76  4680.3 1551.52  4740.3 1550.35
  4770.3 1548.39  4827.6 1546.81  4860.3 1545.33  4900.3 1545.19  4940.3 1545.76
  4963.6 1543.89  4980.3 1542.34  4988.1 1540.31  4988.4 1539.81  4992.2 1539.81
  4992.5 1540.31  4999.1 1542.54  5002.8 1542.54  5008.2 1544.62  5030.3 1546.69
  5070.3 1548.24  5090.3 1549.61  5120.3 1547.41  5140.3 1547.94  5252.9 1546.89
#Mann=5,-1,0
  4413.0    0.07       0  4827.6    0.16       0  4963.6    0.07       0
  4988.1    0.07       0  4992.5    0.07       0
Bank Sta=4988.1,4992.5
Exp/Cntr=0.3,0.1

Type RM Length L Ch R = 1,3598,273,273,273
BEGIN DESCRIPTION:
Mapping XS e5b58254
END DESCRIPTION:
XS GIS Cut Line= 3
      1627732.47      6970163.34      1627750.70      6970695.92
      1627750.70      6970904.23
#Sta/Elev= 30
  4468.3 1553.49  4503.0 1552.83  4526.2 1553.93  4543.0 1554.58  4583.0 1553.26
  4623.0 1554.85  4643.1 1554.24  4663.1 1554.77  4673.1 1553.92  4693.2 1555.48
  4703.1 1554.86  4713.1 1555.44  4763.1 1552.76  4783.1 1549.62  4883.2 1545.61
  4923.2 1544.73  4953.2 1540.82  4961.0 1540.44  4961.3 1539.94  4965.5 1540.44
  4973.3 1540.45  4979.5 1541.83  4984.5 1541.39  4993.3 1542.52  5013.3 1541.86
  5043.3 1543.75  5109.6 1545.97  5133.3 1546.42  5153.3 1545.16  5209.5 1546.02
#Mann=5,-1,0
  4468.3   0.035       0  4526.2    0.07       0  4961.0    0.07       0
  4965.5    0.07       0  5109.6    0.16       0
Bank Sta=4961,4965.5
Exp/Cntr=0.3,0.1

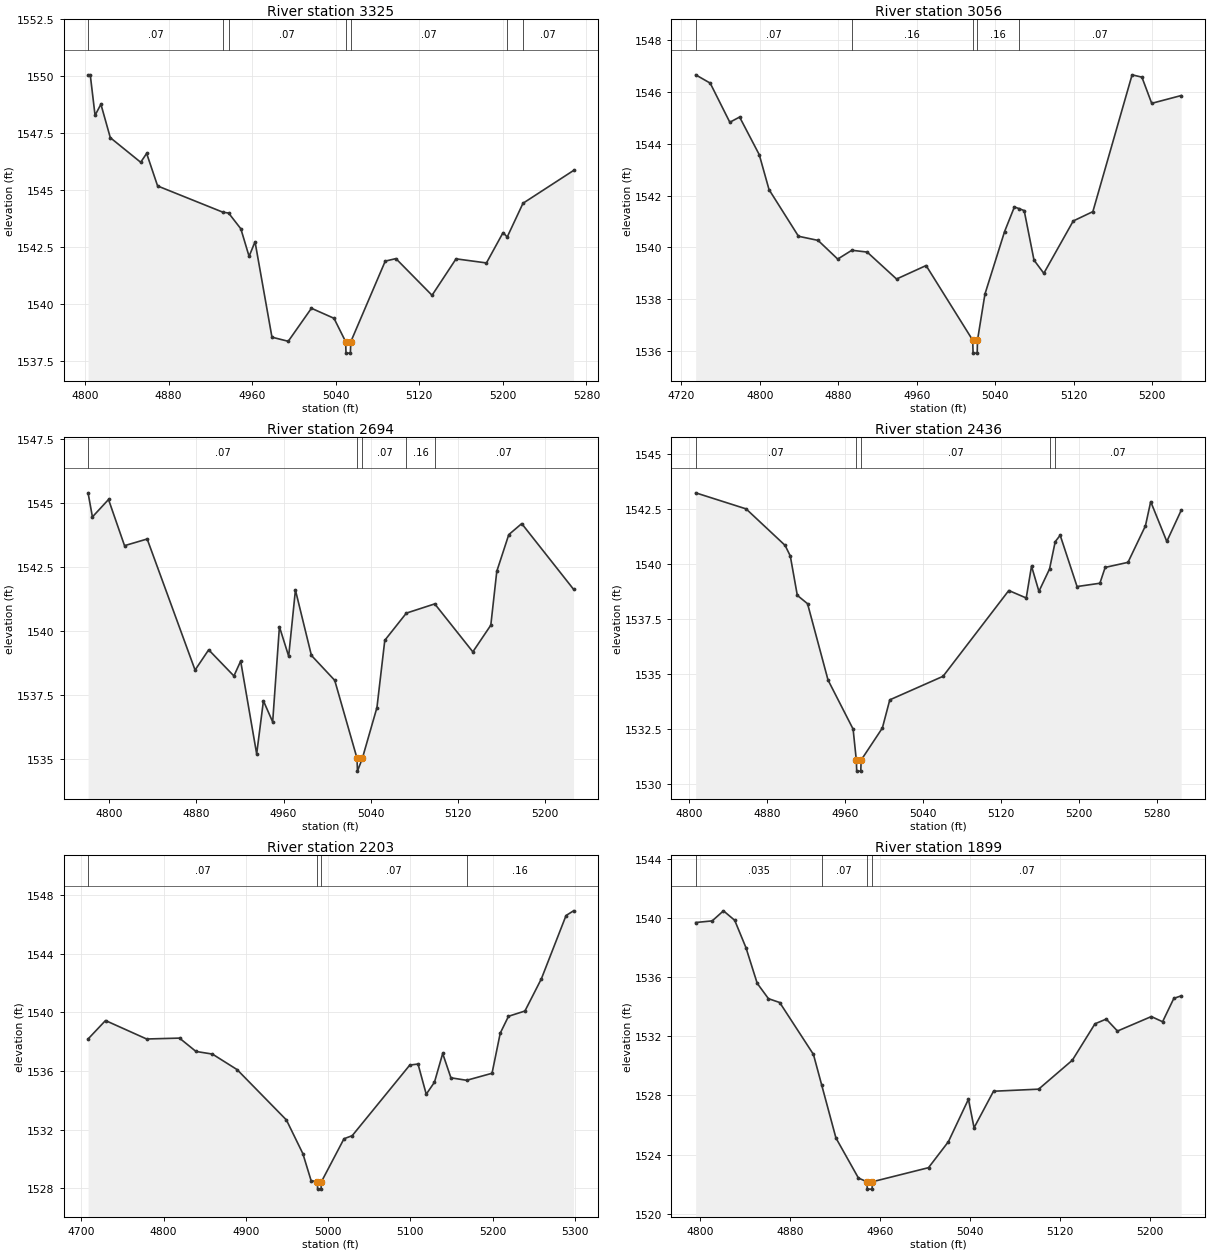
Type RM Length L Ch R = 1,3325,269,269,269
BEGIN DESCRIPTION:
Mapping XS 28fe1dc7
END DESCRIPTION:
XS GIS Cut Line= 3
      1627346.25      6970728.70      1627519.89      6970822.46
      1627753.05      6970953.72
#Sta/Elev= 30
  4802.8 1550.07  4804.9 1550.07  4809.5 1548.29  4815.1 1548.78  4824.1 1547.31
  4853.2 1546.23  4858.9 1546.62  4869.4 1545.19  4931.8 1544.04  4937.4 1544.00
  4949.1 1543.31  4957.0 1542.10  4962.7 1542.74  4978.9 1538.55  4994.5 1538.37
  5016.7 1539.82  5038.3 1539.38  5049.5 1538.35  5049.8 1537.85  5054.0 1537.85
  5054.4 1538.35  5087.4 1541.89  5097.6 1542.00  5132.2 1540.39  5155.2 1541.99
  5184.3 1541.81  5200.2 1543.14  5204.2 1542.95  5219.3 1544.43  5267.7 1545.87
#Mann=7,-1,0
  4802.8    0.07       0  4931.8    0.12       0  4937.4    0.07       0
  5049.5    0.07       0  5054.4    0.07       0  5204.2    0.16       0
  5219.3    0.07       0
Bank Sta=5049.5,5054.4
Exp/Cntr=0.3,0.1

Type RM Length L Ch R = 1,3056,362,362,362
BEGIN DESCRIPTION:
Mapping XS 213be7a8
END DESCRIPTION:
XS GIS Cut Line= 3
      1627340.22      6971042.95      1627604.96      6971049.89
      1627835.03      6971049.89
#Sta/Elev= 30
  4734.6 1546.66  4749.4 1546.34  4769.4 1544.83  4779.4 1545.03  4799.4 1543.58
  4809.4 1542.23  4839.4 1540.43  4859.4 1540.27  4879.4 1539.55  4893.8 1539.89
  4909.4 1539.82  4939.4 1538.78  4969.5 1539.30  5017.0 1536.42  5017.4 1535.92
  5021.6 1535.92  5021.9 1536.42  5029.5 1538.20  5049.5 1540.61  5059.5 1541.56
  5064.1 1541.50  5069.5 1541.42  5079.5 1539.51  5089.5 1539.00  5119.5 1541.02
  5139.5 1541.38  5179.5 1546.66  5189.5 1546.57  5199.5 1545.56  5229.5 1545.86
#Mann=5,-1,0
  4734.6    0.07       0  4893.8    0.16       0  5017.0    0.07       0
  5021.9    0.16       0  5064.1    0.07       0
Bank Sta=5017,5021.9
Exp/Cntr=0.3,0.1

Type RM Length L Ch R = 1,2694,258,258,258
BEGIN DESCRIPTION:
Mapping XS afb78732
END DESCRIPTION:
XS GIS Cut Line= 3
      1627345.30      6971384.34      1627523.29      6971255.84
      1627729.04      6971161.21
#Sta/Elev= 30
  4780.4 1545.39  4784.4 1544.45  4799.2 1545.13  4813.9 1543.33  4834.7 1543.59
  4878.7 1538.48  4891.2 1539.27  4914.4 1538.25  4920.6 1538.83  4935.3 1535.21
  4941.5 1537.28  4950.0 1536.46  4956.2 1540.17  4964.7 1539.02  4970.9 1541.60
  4985.6 1539.05  5007.0 1538.08  5027.5 1535.04  5027.9 1534.54  5032.4 1535.04
  5045.8 1537.02  5053.0 1539.64  5072.8 1540.70  5098.9 1541.06  5133.9 1539.19
  5150.4 1540.23  5155.9 1542.33  5166.9 1543.76  5178.8 1544.19  5226.4 1541.63
#Mann=5,-1,0
  4780.4    0.07       0  5027.5    0.07       0  5032.4    0.07       0
  5072.8    0.16       0  5098.9    0.07       0
Bank Sta=5027.5,5032.4
Exp/Cntr=0.3,0.1

Type RM Length L Ch R = 1,2436,233,233,233
BEGIN DESCRIPTION:
Mapping XS 32e64d70
END DESCRIPTION:
XS GIS Cut Line= 3
      1627355.73      6971531.89      1627538.05      6971473.72
      1627818.47      6971350.44
#Sta/Elev= 30
  4807.1 1543.23  4858.8 1542.50  4898.8 1540.84  4904.1 1540.36  4911.3 1538.57
  4921.8 1538.19  4942.8 1534.72  4968.5 1532.49  4971.8 1531.08  4972.2 1530.58
  4976.4 1530.58  4976.7 1531.08  4998.5 1532.54  5006.1 1533.82  5060.7 1534.89
  5128.1 1538.79  5146.0 1538.45  5151.4 1539.90  5159.0 1538.75  5169.9 1539.77
  5175.7 1541.01  5180.8 1541.30  5198.1 1538.97  5221.5 1539.12  5226.9 1539.84
  5250.3 1540.07  5268.2 1541.73  5273.6 1542.83  5290.1 1541.02  5304.8 1542.43
#Mann=5,-1,0
  4807.1    0.07       0  4971.8    0.07       0  4976.7    0.07       0
  5169.9    0.16       0  5175.7    0.07       0
Bank Sta=4971.8,4976.7
Exp/Cntr=0.3,0.1

Type RM Length L Ch R = 1,2203,304,304,304
BEGIN DESCRIPTION:
Mapping XS 4ebad9eb
END DESCRIPTION:
XS GIS Cut Line= 3
      1627363.79      6971660.70      1627654.02      6971660.70
      1627954.07      6971657.23
#Sta/Elev= 30
  4708.2 1538.18  4729.4 1539.44  4779.4 1538.18  4819.4 1538.24  4839.4 1537.33
  4859.4 1537.15  4889.4 1536.09  4949.4 1532.65  4969.4 1530.35  4979.4 1528.51
  4987.0 1528.43  4987.3 1527.93  4991.5 1527.93  4991.9 1528.43  5019.4 1531.37
  5029.4 1531.58  5099.4 1536.40  5109.4 1536.47  5119.4 1534.41  5129.4 1535.23
  5139.4 1537.19  5149.4 1535.53  5168.6 1535.36  5199.4 1535.84  5209.4 1538.58
  5219.4 1539.73  5239.4 1540.09  5259.4 1542.29  5289.4 1546.61  5298.5 1546.93
#Mann=4,-1,0
  4708.2    0.07       0  4987.0    0.07       0  4991.9    0.07       0
  5168.6    0.16       0
Bank Sta=4987,4991.9
Exp/Cntr=0.3,0.1

Type RM Length L Ch R = 1,1899,128,128,128
BEGIN DESCRIPTION:
Mapping XS b33c663a
END DESCRIPTION:
XS GIS Cut Line= 3
      1627250.33      6971868.96      1627454.52      6971865.49
      1627681.48      6971851.69
#Sta/Elev= 30
  4795.8 1539.69  4810.5 1539.80  4820.5 1540.48  4830.5 1539.84  4840.5 1537.99
  4850.5 1535.58  4860.5 1534.54  4870.5 1534.28  4900.5 1530.77  4907.8 1528.71
  4920.5 1525.12  4940.5 1522.41  4948.0 1522.16  4948.4 1521.66  4952.6 1521.66
  4953.0 1522.16  5002.8 1523.11  5020.5 1524.87  5038.3 1527.74  5043.3 1525.81
  5060.6 1528.28  5100.7 1528.42  5130.7 1530.38  5150.8 1532.84  5160.8 1533.16
  5170.8 1532.35  5200.9 1533.33  5210.9 1532.98  5220.9 1534.56  5227.4 1534.73
#Mann=4,-1,0
  4795.8   0.035       0  4907.8    0.07       0  4948.0    0.07       0
  4953.0    0.07       0
Bank Sta=4948,4953
Exp/Cntr=0.3,0.1

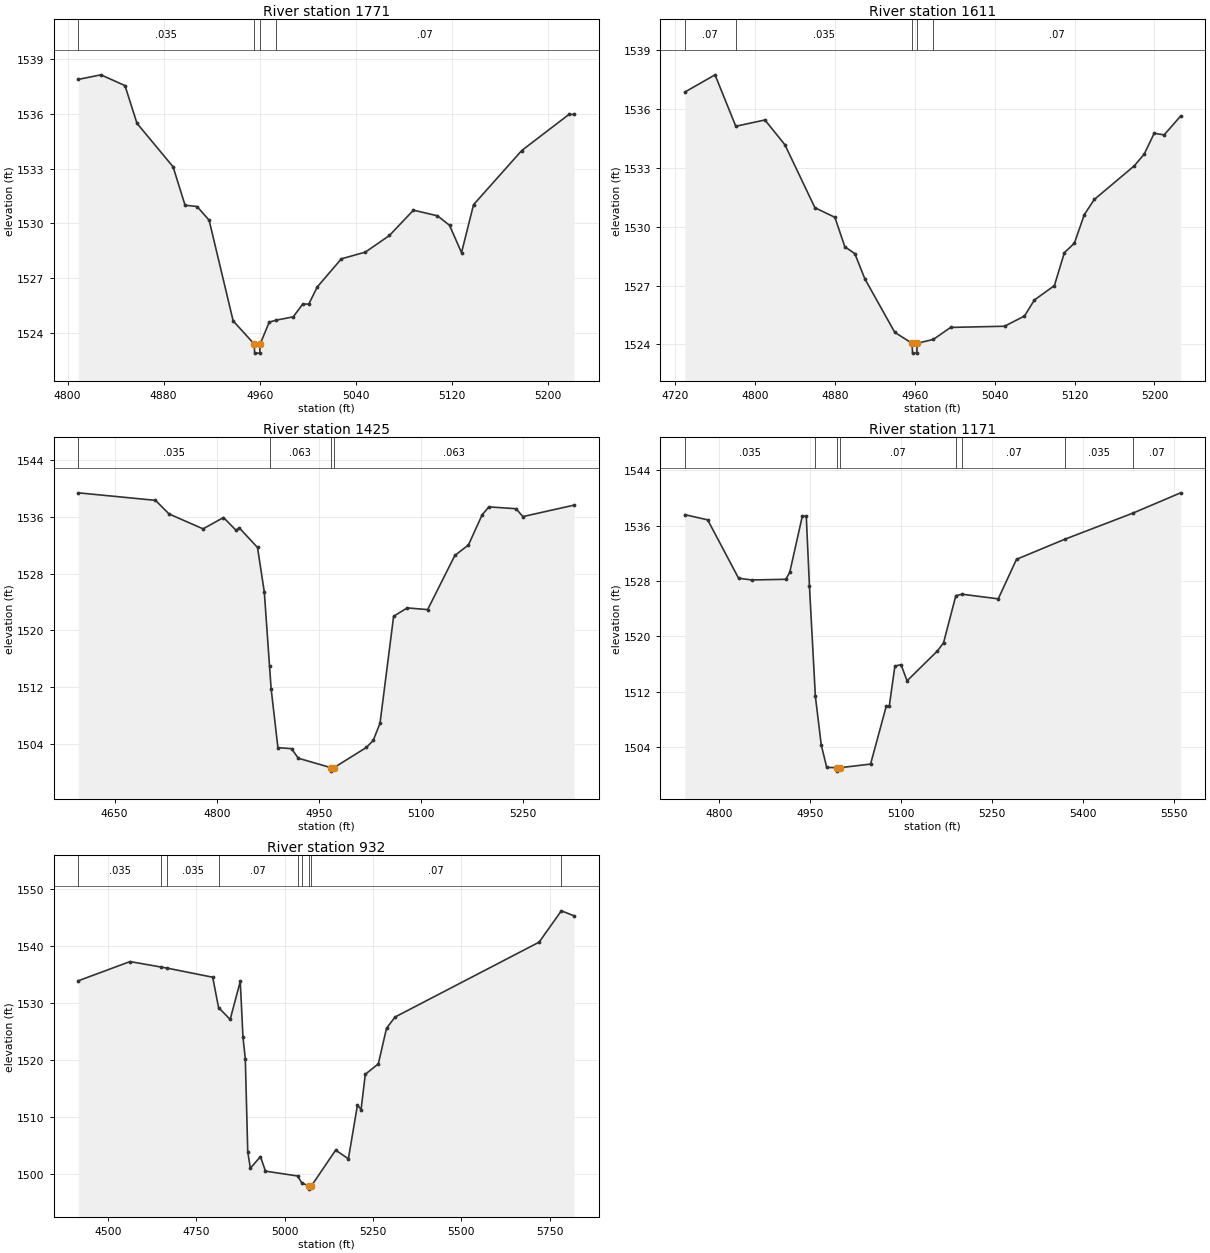
Type RM Length L Ch R = 1,1771,160,160,160
BEGIN DESCRIPTION:
Mapping XS 1f0982cc
END DESCRIPTION:
XS GIS Cut Line= 3
      1627246.18      6971968.96      1627435.77      6971971.05
      1627658.64      6971967.57
#Sta/Elev= 30
  4809.0 1537.90  4827.8 1538.15  4847.8 1537.56  4857.8 1535.49  4887.8 1533.11
  4897.8 1531.00  4907.8 1530.93  4917.8 1530.18  4937.8 1524.66  4955.3 1523.39
  4955.7 1522.89  4959.9 1522.89  4960.3 1523.39  4967.8 1524.59  4973.8 1524.70
  4987.8 1524.88  4995.7 1525.58  5000.7 1525.58  5007.8 1526.52  5027.8 1528.06
  5047.8 1528.43  5067.8 1529.34  5087.8 1530.73  5107.8 1530.42  5117.8 1529.90
  5127.8 1528.40  5137.8 1531.03  5177.9 1534.00  5217.2 1535.98  5221.5 1535.98
#Mann=4,-1,0
  4809.0   0.035       0  4955.3    0.07       0  4960.3   0.035       0
  4973.8    0.07       0
Bank Sta=4955.3,4960.3
Exp/Cntr=0.3,0.1

Type RM Length L Ch R = 1,1611,186,186,186
BEGIN DESCRIPTION:
Mapping XS de528f75
END DESCRIPTION:
XS GIS Cut Line= 3
      1627234.67      6972104.81      1627501.99      6972110.02
      1627731.46      6972104.85
#Sta/Elev= 30
  4729.4 1536.86  4759.7 1537.74  4780.5 1535.12  4809.7 1535.44  4829.7 1534.18
  4859.8 1530.97  4879.8 1530.48  4889.8 1528.98  4899.8 1528.63  4909.8 1527.35
  4939.8 1524.62  4957.2 1524.06  4957.6 1523.56  4961.9 1523.56  4962.3 1524.06
  4978.5 1524.26  4995.8 1524.87  5049.8 1524.93  5069.8 1525.45  5079.8 1526.27
  5099.8 1527.00  5109.8 1528.68  5119.8 1529.16  5129.8 1530.62  5139.8 1531.39
  5179.8 1533.10  5189.8 1533.70  5199.8 1534.76  5209.8 1534.68  5226.3 1535.64
#Mann=5,-1,0
  4729.4    0.07       0  4780.5   0.035       0  4957.2    0.07       0
  4962.3   0.035       0  4978.5    0.07       0
Bank Sta=4957.2,4962.3
Exp/Cntr=0.3,0.1

Type RM Length L Ch R = 1,1425,254,254,254
BEGIN DESCRIPTION:
Mapping XS 00d45bb5
END DESCRIPTION:
XS GIS Cut Line= 3
      1627051.61      6972287.11      1627449.21      6972280.16
      1627780.45      6972280.16
#Sta/Elev= 30
  4596.6 1539.38  4710.0 1538.32  4730.0 1536.40  4780.0 1534.30  4810.0 1535.90
  4828.4 1534.11  4833.4 1534.42  4860.0 1531.68  4870.0 1525.40  4877.7 1514.92
  4880.0 1511.79  4890.0 1503.46  4910.0 1503.32  4920.0 1501.97  4967.5 1500.65
  4967.9 1500.15  4972.6 1500.65  5020.1 1503.49  5030.1 1504.48  5040.1 1506.90
  5060.1 1521.98  5080.1 1523.16  5110.1 1522.92  5150.1 1530.55  5170.1 1532.03
  5190.1 1536.26  5200.1 1537.40  5240.1 1537.14  5250.1 1536.03  5325.5 1537.65
#Mann=4,-1,0
  4596.6   0.035       0  4877.7   0.063       0  4967.5   0.063       0
  4972.6   0.063       0
Bank Sta=4967.5,4972.6
Exp/Cntr=0.3,0.1

Type RM Length L Ch R = 1,1171,239,239,239
BEGIN DESCRIPTION:
Mapping XS 352eafc7
END DESCRIPTION:
XS GIS Cut Line= 3
      1627068.73      6972407.42      1627315.48      6972478.20
      1627874.97      6972439.89
#Sta/Elev= 30
  4743.3 1537.60  4781.0 1536.85  4832.0 1528.40  4853.9 1528.15  4909.8 1528.25
  4916.3 1529.25  4937.1 1537.40  4943.6 1537.38  4948.8 1527.28  4958.6 1511.30
  4968.3 1504.27  4977.3 1501.03  4994.6 1500.99  4995.0 1500.49  4999.7 1500.99
  5049.6 1501.51  5075.4 1509.87  5080.4 1509.88  5089.7 1515.69  5099.8 1515.90
  5109.8 1513.56  5159.9 1517.89  5169.9 1519.06  5190.2 1525.88  5200.5 1526.09
  5260.1 1525.42  5290.2 1531.14  5369.7 1534.04  5482.0 1537.82  5560.8 1540.76
#Mann=8,-1,0
  4743.3   0.035       0  4958.6    0.07       0  4994.6    0.07       0
  4999.7    0.07       0  5190.2   0.035       0  5200.5    0.07       0
  5369.7   0.035       0  5482.0    0.07       0
Bank Sta=4994.6,4999.7
Exp/Cntr=0.3,0.1

Type RM Length L Ch R = 1,932,0,0,0
BEGIN DESCRIPTION:
Mapping XS a6e0e959
END DESCRIPTION:
XS GIS Cut Line= 3
      1626859.35      6972337.54      1627304.80      6972715.35
      1628101.46      6972524.49
#Sta/Elev= 30
  4415.9 1533.95  4562.2 1537.32  4648.7 1536.37  4668.1 1536.16  4796.2 1534.57
  4812.8 1529.25  4845.6 1527.15  4874.2 1533.84  4881.9 1524.02  4888.5 1520.22
  4895.4 1503.90  4902.8 1501.03  4931.3 1503.07  4945.6 1500.52  5036.3 1499.67
  5048.2 1498.48  5069.6 1497.86  5070.0 1497.36  5074.8 1497.86  5144.2 1504.21
  5180.2 1502.68  5205.9 1512.13  5216.1 1511.33  5228.1 1517.53  5265.0 1519.36
  5288.1 1525.60  5312.2 1527.58  5720.0 1540.73  5782.9 1546.23  5819.2 1545.35
#Mann=9,-1,0
  4415.9   0.035       0  4648.7    0.07       0  4668.1   0.035       0
  4812.8    0.07       0  5036.3   0.035       0  5048.2    0.07       0
  5069.6    0.07       0  5074.8    0.07       0  5782.9   0.035       0
Bank Sta=5069.6,5074.8
Exp/Cntr=0.3,0.1

Chan Stop Cuts=-1