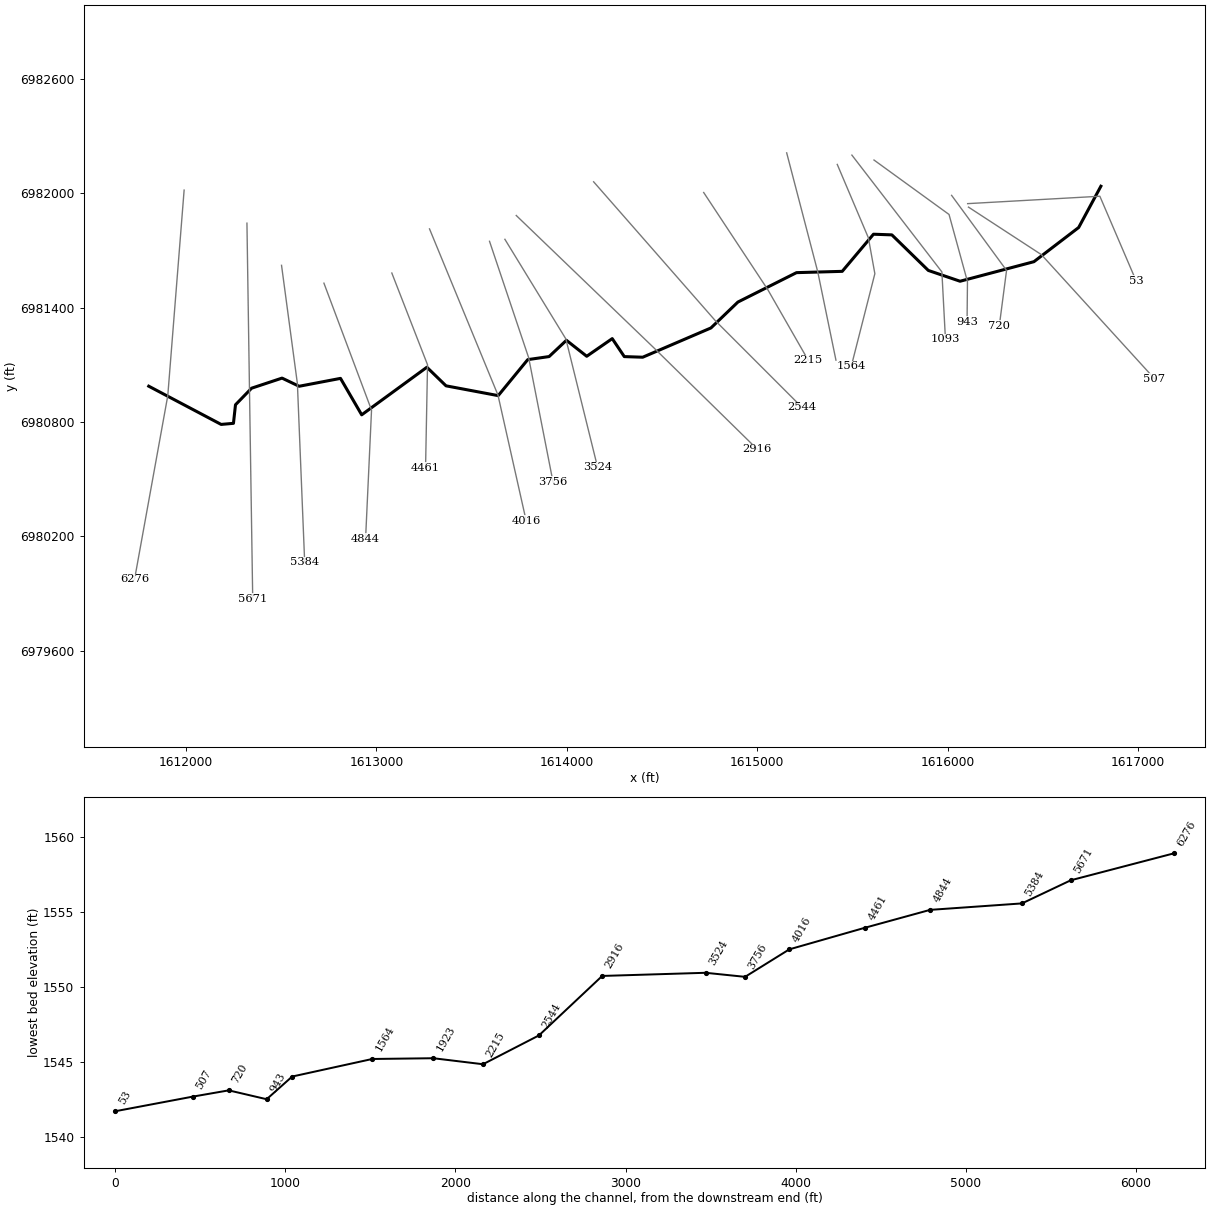
--- Chimney Creek 1129.prj (project) ---

Proj Title=Chimney Creek 1129 Base Level Engineering
Current Plan=p01
Default Exp/Contr=0.3,0.1
English Units
Geom File=g01
Flow File=f01
Plan File=p01
BEGIN DESCRIPTION:
Chimney Creek 1129
END DESCRIPTION:

--- Chimney Creek 1129.p01 (plan) ---

Plan Title=Multiple Run
Short Identifier=Multiple
Geom File=g01
Flow File=f01
Subcritical Flow
K Sum by GR= 0
Std Step Tol= 0.01
Critical Tol= 0.01
Num of Std Step Trials= 20
Max Error Tol= 0.3
Flow Tol Ratio= 0.001
Split Flow NTrial= 30
Split Flow Tol= 0.02
Split Flow Ratio= 0.02
Log Output Level= 0
Friction Slope Method= 1
Unsteady Friction Slope Method= 2
Unsteady Bridges Friction Slope Method= 1
Parabolic Critical Depth
Global Vel Dist=  1 , 1 , 1
Global Log Level= 0
CheckData=True
Encroach Param= -1, 0, 0, 0
BEGIN DESCRIPTION:
Multiple Run
END DESCRIPTION:

--- Chimney Creek 1129.f01 (steady flow) ---

Flow Title=Multiple
Number of Profiles=7
Profile Names=10-year,25-year,50-year,1pct_min,100-year,1pct_plu,500-year
River Rch & RM= Chimney Creek 11,Reach-1,6276
     248     339     414     251     502    1001     746
River Rch & RM= Chimney Creek 11,Reach-1,4016
     298     410     503     307     612    1221     917
River Rch & RM= Chimney Creek 11,Reach-1,507
     327     453     557     341     679    1356    1024
Boundary for River Rch & Prof#=Chimney Creek 11,Reach-1,1
Up Type=0
Dn Type=3
Dn Slope=0.005
Boundary for River Rch & Prof#=Chimney Creek 11,Reach-1,2
Up Type=0
Dn Type=3
Dn Slope=0.005
Boundary for River Rch & Prof#=Chimney Creek 11,Reach-1,3
Up Type=0
Dn Type=3
Dn Slope=0.005
Boundary for River Rch & Prof#=Chimney Creek 11,Reach-1,4
Up Type=0
Dn Type=3
Dn Slope=0.005
Boundary for River Rch & Prof#=Chimney Creek 11,Reach-1,5
Up Type=0
Dn Type=3
Dn Slope=0.005
Boundary for River Rch & Prof#=Chimney Creek 11,Reach-1,6
Up Type=0
Dn Type=3
Dn Slope=0.005
Boundary for River Rch & Prof#=Chimney Creek 11,Reach-1,7
Up Type=0
Dn Type=3
Dn Slope=0.005

--- Chimney Creek 1129.g01 (geometry) ---

Geom Title=Existing Conditions

River Reach=Chimney Creek 11,Reach-1
Reach XY= 30
      1611805.00      6980988.00      1612185.17      6980787.22
      1612249.89      6980792.95      1612260.54      6980890.38
      1612345.19      6980977.49      1612505.00      6981030.44
      1612594.80      6980987.59      1612812.07      6981029.01
      1612923.26      6980837.64      1613265.68      6981087.47
      1613366.15      6980989.87      1613640.12      6980938.44
      1613795.21      6981127.48      1613907.43      6981143.55
      1613998.34      6981229.01      1614105.00      6981145.11
      1614238.96      6981237.81      1614302.34      6981143.34
      1614399.03      6981140.14      1614757.30      6981293.83
      1614898.94      6981429.86      1615206.55      6981584.25
      1615446.70      6981591.07      1615610.89      6981786.04
      1615707.43      6981782.60      1615898.83      6981595.86
      1616065.55      6981539.10      1616453.42      6981641.82
      1616688.35      6981821.33      1616805.00      6982038.00

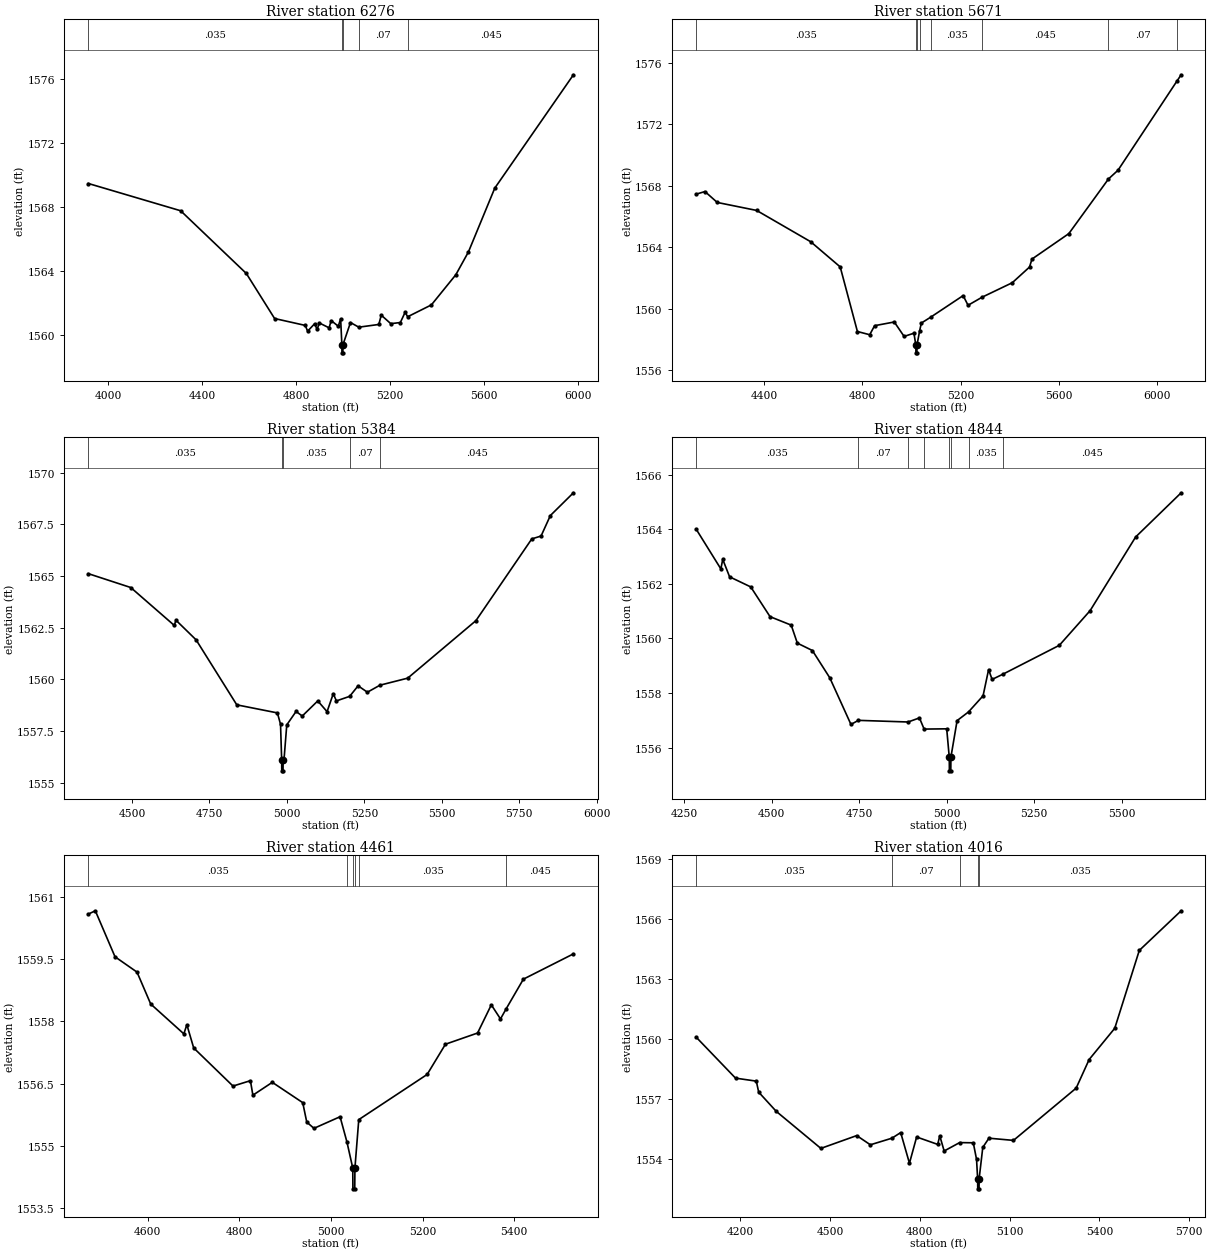
Type RM Length L Ch R = 1,6276,605,605,605
BEGIN DESCRIPTION:
Chimney Creek 1129 9.0
END DESCRIPTION:
XS GIS Cut Line= 3
      1611990.83      6982017.76      1611905.00      6980938.00
      1611730.42      6979973.54
#Sta/Elev= 30
  3916.9 1569.47  4309.5 1567.77  4588.8 1563.86  4709.1 1561.05  4839.6 1560.62
  4849.6 1560.26  4879.7 1560.73  4889.7 1560.37  4899.7 1560.77  4940.9 1560.47
  4949.9 1560.92  4980.0 1560.57  4990.0 1561.03  4995.3 1559.41  4995.6 1558.91
  4999.5 1558.91  4999.8 1559.41  5031.9 1560.80  5067.3 1560.51  5152.5 1560.68
  5162.7 1561.26  5203.3 1560.73  5244.0 1560.80  5264.3 1561.44  5275.1 1561.16
  5376.1 1561.90  5480.0 1563.78  5533.5 1565.20  5645.6 1569.18  5980.2 1576.25
#Mann=5,-1,0
  3916.9   0.035       0  4995.3   0.035       0  4999.8   0.035       0
  5067.3    0.07       0  5275.1   0.045       0
Bank Sta=4995.3,4999.8
Exp/Cntr=0.3,0.1

Type RM Length L Ch R = 1,5671,287,287,287
BEGIN DESCRIPTION:
Mapping XS 07b9b858
END DESCRIPTION:
XS GIS Cut Line= 3
      1612320.70      6981844.13      1612333.72      6980989.13
      1612351.05      6979871.16
#Sta/Elev= 30
  4123.4 1567.46  4159.5 1567.63  4209.5 1566.92  4369.6 1566.40  4589.6 1564.36
  4709.6 1562.72  4779.6 1558.51  4829.6 1558.30  4849.6 1558.89  4929.6 1559.13
  4969.6 1558.19  5009.6 1558.40  5017.3 1557.62  5017.7 1557.12  5021.6 1557.12
  5021.9 1557.62  5032.4 1558.53  5039.6 1559.06  5078.3 1559.45  5209.7 1560.85
  5229.7 1560.22  5287.3 1560.75  5409.7 1561.69  5479.7 1562.71  5489.7 1563.23
  5639.7 1564.89  5800.9 1568.45  5839.7 1569.02  6080.7 1574.86  6096.6 1575.24
#Mann=8,-1,0
  4123.4   0.035       0  5017.3   0.035       0  5021.9   0.035       0
  5032.4    0.07       0  5078.3   0.035       0  5287.3   0.045       0
  5800.9    0.07       0  6080.7   0.045       0
Bank Sta=5017.3,5021.9
Exp/Cntr=0.3,0.1

Type RM Length L Ch R = 1,5384,540,540,540
BEGIN DESCRIPTION:
Mapping XS b6192215
END DESCRIPTION:
XS GIS Cut Line= 3
      1612502.34      6981622.72      1612585.67      6981001.20
      1612623.87      6980063.66
#Sta/Elev= 30
  4359.4 1565.11  4496.3 1564.44  4636.6 1562.61  4642.2 1562.86  4707.2 1561.91
  4838.4 1558.77  4969.5 1558.38  4979.6 1557.83  4983.3 1556.08  4983.6 1555.58
  4987.6 1555.58  4987.9 1556.08  4990.6 1556.08  4999.7 1557.80  5029.7 1558.45
  5049.7 1558.23  5099.8 1558.96  5129.8 1558.44  5149.8 1559.31  5159.8 1558.96
  5202.7 1559.18  5229.9 1559.69  5259.9 1559.38  5300.5 1559.72  5390.0 1560.06
  5610.2 1562.84  5790.4 1566.79  5820.4 1566.93  5850.4 1567.92  5924.8 1569.02
#Mann=5,-1,0
  4359.4   0.035       0  4983.3   0.035       0  4987.9   0.035       0
  5202.7    0.07       0  5300.5   0.045       0
Bank Sta=4983.3,4987.9
Exp/Cntr=0.3,0.1

Type RM Length L Ch R = 1,4844,383,383,383
BEGIN DESCRIPTION:
Mapping XS fbca77fe
END DESCRIPTION:
XS GIS Cut Line= 3
      1612725.01      6981529.03      1612974.99      6980862.39
      1612943.74      6980187.88
#Sta/Elev= 30
  4283.3 1564.01  4354.1 1562.55  4359.5 1562.90  4379.1 1562.26  4439.6 1561.89
  4494.8 1560.80  4555.3 1560.49  4572.8 1559.83  4615.8 1559.56  4665.6 1558.56
  4726.2 1556.85  4747.3 1557.00  4889.6 1556.94  4922.0 1557.09  4935.4 1556.68
  5000.0 1556.69  5007.3 1555.65  5007.7 1555.15  5011.7 1555.15  5012.0 1555.65
  5029.7 1556.99  5062.4 1557.31  5104.0 1557.90  5119.8 1558.86  5129.8 1558.50
  5160.5 1558.69  5322.1 1559.75  5410.1 1561.02  5540.3 1563.72  5670.5 1565.34
#Mann=8,-1,0
  4283.3   0.035       0  4747.3    0.07       0  4889.6   0.035       0
  4935.4    0.07       0  5007.3    0.07       0  5012.0    0.07       0
  5062.4   0.035       0  5160.5   0.045       0
Bank Sta=5007.3,5012
Exp/Cntr=0.3,0.1

Type RM Length L Ch R = 1,4461,445,445,445
BEGIN DESCRIPTION:
Mapping XS 16665d81
END DESCRIPTION:
XS GIS Cut Line= 3
      1613081.55      6981582.20      1613269.05      6981100.45
      1613258.63      6980558.80
#Sta/Elev= 30
  4470.5 1560.59  4485.7 1560.67  4528.7 1559.56  4576.7 1559.19  4606.6 1558.42
  4678.9 1557.70  4685.5 1557.92  4700.4 1557.36  4786.2 1556.44  4824.2 1556.57
  4829.6 1556.22  4872.0 1556.53  4938.4 1556.04  4947.2 1555.57  4962.9 1555.42
  5019.9 1555.70  5034.9 1555.09  5047.6 1554.46  5047.9 1553.96  5051.9 1553.96
  5052.3 1554.46  5060.7 1555.63  5209.9 1556.72  5249.9 1557.45  5320.0 1557.72
  5350.0 1558.40  5370.0 1558.06  5382.7 1558.31  5420.0 1559.02  5529.2 1559.63
#Mann=6,-1,0
  4470.5   0.035       0  5034.9    0.07       0  5047.6   0.035       0
  5052.3    0.07       0  5060.7   0.035       0  5382.7   0.045       0
Bank Sta=5047.6,5052.3
Exp/Cntr=0.3,0.1

Type RM Length L Ch R = 1,4016,260,260,260
BEGIN DESCRIPTION:
Mapping XS 7b82b62c
END DESCRIPTION:
XS GIS Cut Line= 3
      1613279.48      6981813.96      1613638.84      6980941.59
      1613786.95      6980281.59
#Sta/Elev= 30
  4053.2 1560.10  4184.9 1558.05  4254.3 1557.90  4262.2 1557.35  4320.9 1556.39
  4469.9 1554.54  4589.6 1555.18  4635.2 1554.72  4707.2 1555.05  4736.4 1555.33
  4765.7 1553.80  4789.7 1555.11  4860.0 1554.74  4866.9 1555.17  4881.6 1554.41
  4933.3 1554.83  4978.9 1554.82  4989.8 1553.99  4993.4 1553.02  4993.8 1552.52
  4998.1 1552.52  4998.4 1553.02  5010.6 1554.59  5031.1 1555.05  5113.1 1554.94
  5322.4 1557.55  5365.8 1558.98  5451.3 1560.54  5533.3 1564.43  5673.1 1566.41
#Mann=5,-1,0
  4053.2   0.035       0  4707.2    0.07       0  4933.3   0.035       0
  4993.4   0.035       0  4998.4   0.035       0
Bank Sta=4993.4,4998.4
Exp/Cntr=0.3,0.1

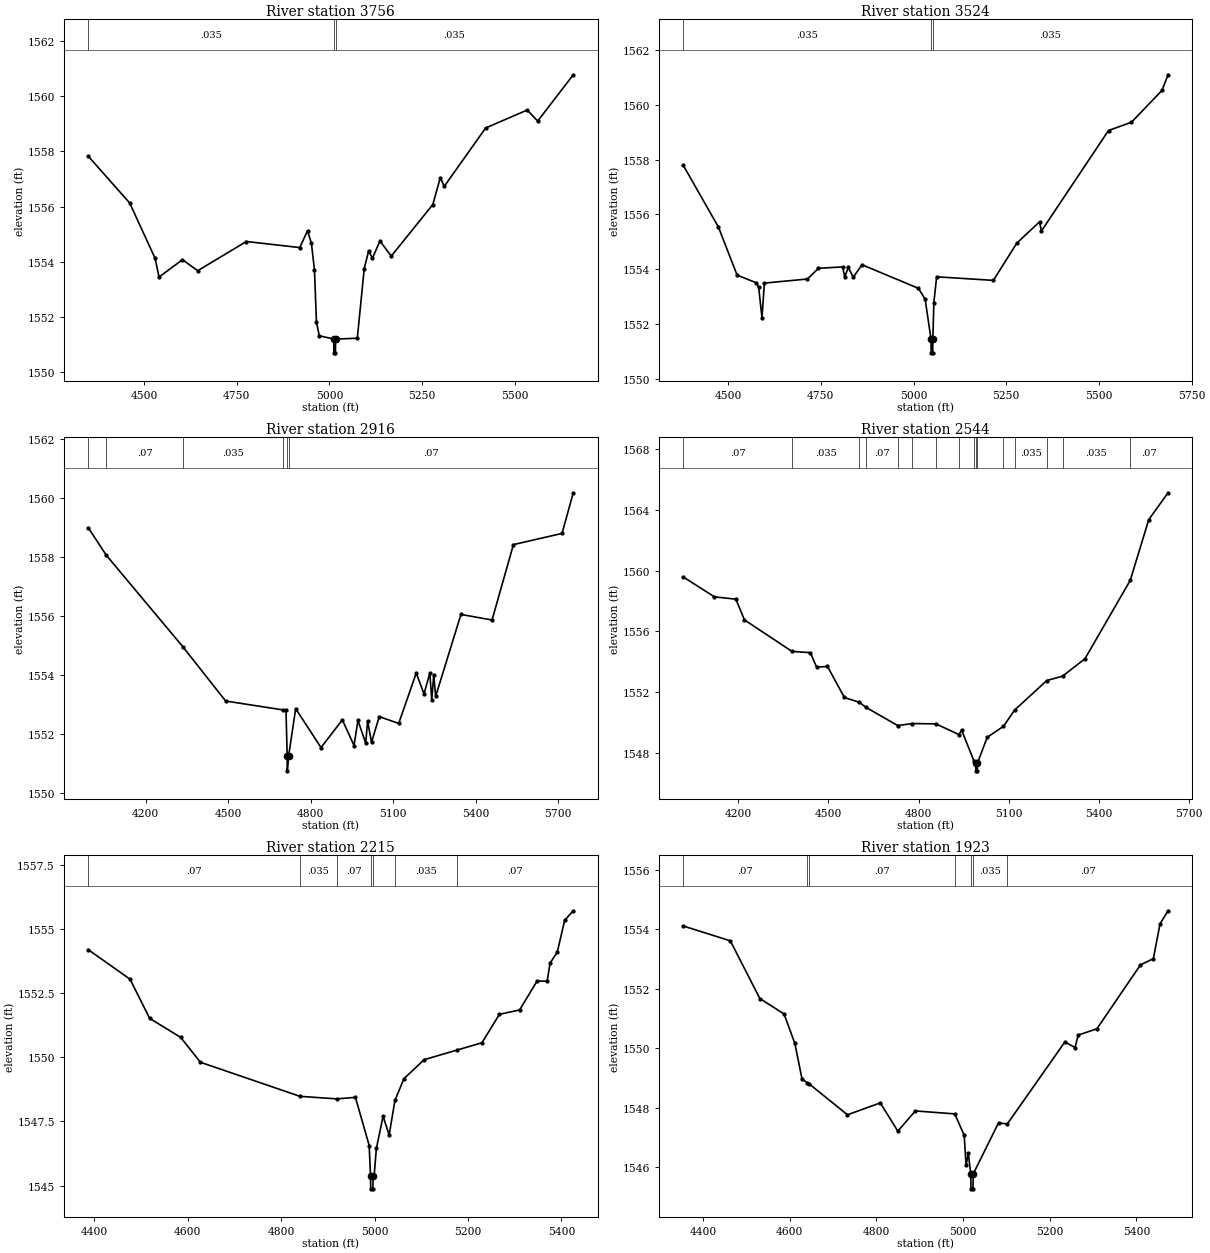
Type RM Length L Ch R = 1,3756,232,232,232
BEGIN DESCRIPTION:
Mapping XS 92b9e798
END DESCRIPTION:
XS GIS Cut Line= 3
      1613594.58      6981748.84      1613800.30      6981136.91
      1613927.90      6980485.88
#Sta/Elev= 30
  4349.1 1557.82  4460.5 1556.13  4529.3 1554.12  4539.9 1553.44  4603.2 1554.07
  4644.3 1553.67  4775.7 1554.73  4919.7 1554.51  4940.8 1555.12  4951.3 1554.66
  4959.5 1553.70  4964.8 1551.81  4972.4 1551.31  5011.5 1551.19  5011.8 1550.69
  5016.1 1550.69  5016.5 1551.19  5075.1 1551.22  5093.8 1553.74  5105.7 1554.39
  5115.9 1554.12  5136.2 1554.75  5166.8 1554.20  5278.9 1556.07  5299.3 1557.05
  5309.8 1556.73  5421.6 1558.85  5533.7 1559.50  5562.1 1559.10  5658.1 1560.78
#Mann=3,-1,0
  4349.1   0.035       0  5011.5   0.035       0  5016.5   0.035       0
Bank Sta=5011.5,5016.5
Exp/Cntr=0.3,0.1

Type RM Length L Ch R = 1,3524,608,608,608
BEGIN DESCRIPTION:
Mapping XS 2fb0a9b2
END DESCRIPTION:
XS GIS Cut Line= 3
      1613675.29      6981759.32      1613995.61      6981235.86
      1614162.07      6980562.21
#Sta/Elev= 30
  4378.7 1557.80  4474.0 1555.54  4524.3 1553.79  4576.5 1553.51  4582.4 1553.35
  4591.3 1552.24  4597.8 1553.50  4713.9 1553.65  4743.7 1554.04  4808.7 1554.09
  4814.5 1553.73  4824.1 1554.07  4837.5 1553.71  4860.9 1554.17  5013.3 1553.31
  5031.4 1552.91  5047.1 1551.46  5047.5 1550.96  5051.8 1550.96  5052.1 1551.46
  5054.8 1552.79  5062.3 1553.73  5215.4 1553.60  5278.6 1554.96  5339.7 1555.73
  5344.9 1555.40  5525.8 1559.06  5587.6 1559.36  5670.0 1560.52  5686.3 1561.09
#Mann=3,-1,0
  4378.7   0.035       0  5047.1   0.035       0  5052.1   0.035       0
Bank Sta=5047.1,5052.1
Exp/Cntr=0.3,0.1

Type RM Length L Ch R = 1,2916,372,372,372
BEGIN DESCRIPTION:
Mapping XS 44e331b4
END DESCRIPTION:
XS GIS Cut Line= 3
      1613734.95      6981884.34      1614457.20      6981189.87
      1615001.14      6980656.32
#Sta/Elev= 30
  3991.7 1559.00  4057.0 1558.07  4334.8 1554.97  4491.2 1553.12  4698.9 1552.82
  4710.6 1552.81  4715.0 1551.25  4715.4 1550.75  4720.1 1551.25  4745.9 1552.86
  4838.0 1551.54  4915.7 1552.48  4958.1 1551.61  4972.3 1552.46  5000.5 1551.69
  5007.5 1552.44  5021.7 1551.72  5050.0 1552.59  5120.7 1552.36  5184.4 1554.07
  5212.7 1553.36  5233.8 1554.07  5241.0 1553.15  5248.0 1554.01  5255.1 1553.28
  5347.0 1556.06  5460.1 1555.87  5537.9 1558.43  5714.7 1558.81  5755.6 1560.19
#Mann=6,-1,0
  3991.7   0.035       0  4057.0    0.07       0  4334.8   0.035       0
  4698.9    0.07       0  4715.0    0.07       0  4720.1    0.07       0
Bank Sta=4715,4720.1
Exp/Cntr=0.3,0.1

Type RM Length L Ch R = 1,2544,329,329,329
BEGIN DESCRIPTION:
Mapping XS 47e0d055
END DESCRIPTION:
XS GIS Cut Line= 3
      1614141.25      6982061.36      1614780.12      6981332.23
      1615234.98      6980877.36
#Sta/Elev= 30
  4016.7 1559.59  4121.0 1558.27  4192.1 1558.12  4220.6 1556.75  4378.8 1554.67
  4439.8 1554.59  4460.7 1553.63  4496.8 1553.68  4553.0 1551.63  4603.2 1551.31
  4623.8 1550.99  4730.3 1549.78  4779.0 1549.91  4857.4 1549.89  4934.3 1549.18
  4942.8 1549.48  4984.5 1547.41  4989.9 1547.29  4990.3 1546.79  4994.9 1546.79
  4995.4 1547.29  5027.9 1549.00  5082.1 1549.73  5119.1 1550.80  5226.2 1552.75
  5278.8 1553.04  5353.2 1554.19  5503.7 1559.36  5565.3 1563.37  5629.4 1565.14
#Mann=16,-1,0
  4016.7    0.07       0  4378.8   0.035       0  4603.2   0.063       0
  4623.8    0.07       0  4730.3   0.035       0  4779.0    0.07       0
  4857.4   0.035       0  4934.3    0.07       0  4984.5   0.035       0
  4989.9   0.035       0  4995.4   0.035       0  5082.1    0.07       0
  5119.1   0.035       0  5226.2    0.07       0  5278.8   0.035       0
  5503.7    0.07       0
Bank Sta=4989.9,4995.4
Exp/Cntr=0.3,0.1

Type RM Length L Ch R = 1,2215,292,292,292
BEGIN DESCRIPTION:
Mapping XS 6f5fa1f2
END DESCRIPTION:
XS GIS Cut Line= 3
      1614719.27      6982005.03      1615056.08      6981494.60
      1615267.89      6981124.81
#Sta/Elev= 30
  4387.5 1554.20  4476.7 1553.05  4518.8 1551.52  4585.1 1550.78  4627.2 1549.81
  4840.3 1548.48  4919.3 1548.38  4959.0 1548.44  4988.5 1546.56  4991.3 1545.37
  4991.7 1544.87  4996.3 1544.87  4996.8 1545.37  4999.0 1545.37  5003.9 1546.45
  5018.2 1547.70  5031.2 1546.97  5043.6 1548.32  5062.9 1549.17  5106.1 1549.91
  5175.5 1550.28  5229.8 1550.57  5267.2 1551.68  5310.4 1551.85  5347.8 1552.98
  5369.4 1552.97  5375.4 1553.67  5391.0 1554.11  5406.8 1555.35  5425.2 1555.72
#Mann=7,-1,0
  4387.5    0.07       0  4840.3   0.035       0  4919.3    0.07       0
  4991.3    0.07       0  4996.8    0.07       0  5043.6   0.035       0
  5175.5    0.07       0
Bank Sta=4991.3,4996.8
Exp/Cntr=0.3,0.1

Type RM Length L Ch R = 1,1923,359,359,359
BEGIN DESCRIPTION:
Mapping XS ca76c27d
END DESCRIPTION:
XS GIS Cut Line= 3
      1615155.04      6982213.36      1615318.24      6981588.35
      1615413.72      6981124.84
#Sta/Elev= 30
  4353.7 1554.11  4462.6 1553.61  4530.7 1551.67  4586.6 1551.15  4611.6 1550.16
  4628.0 1548.97  4640.5 1548.83  4643.7 1548.81  4733.0 1547.76  4808.8 1548.16
  4849.2 1547.21  4889.7 1547.89  4980.7 1547.79  5002.4 1547.07  5006.8 1546.06
  5011.9 1546.46  5017.6 1545.77  5018.1 1545.27  5022.8 1545.27  5023.2 1545.77
  5081.7 1547.49  5101.8 1547.45  5234.8 1550.21  5258.3 1550.02  5265.5 1550.44
  5308.6 1550.65  5409.2 1552.80  5439.0 1553.01  5454.4 1554.18  5472.9 1554.62
#Mann=7,-1,0
  4353.7    0.07       0  4640.5   0.035       0  4643.7    0.07       0
  4980.7   0.035       0  5017.6   0.035       0  5023.2   0.035       0
  5101.8    0.07       0
Bank Sta=5017.6,5023.2
Exp/Cntr=0.3,0.1

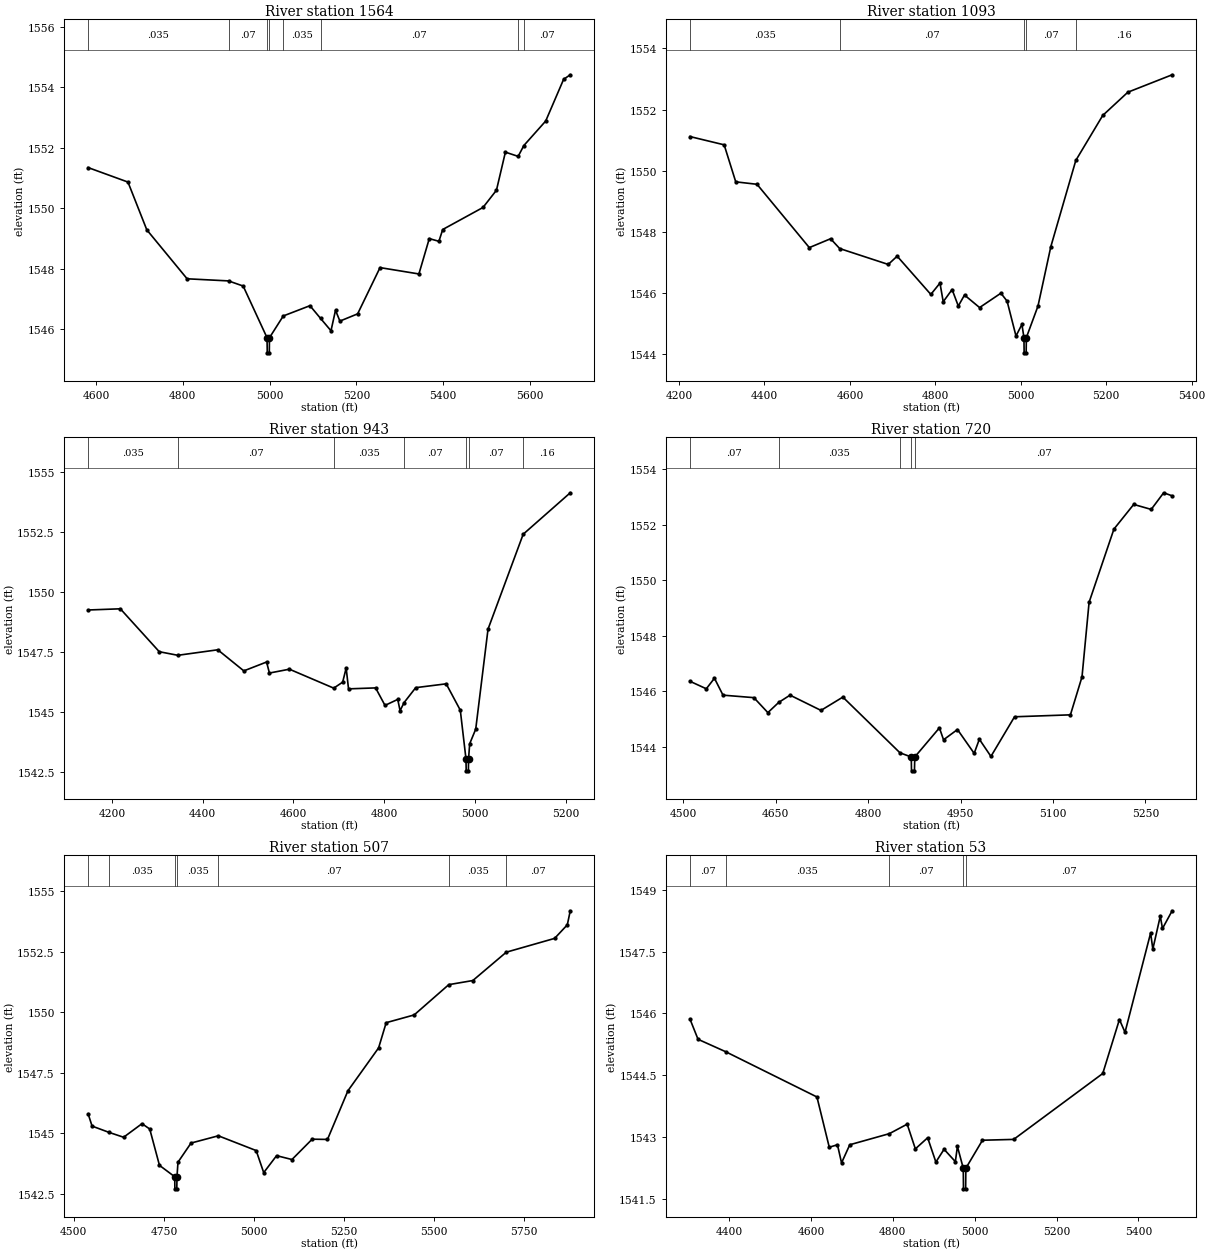
Type RM Length L Ch R = 1,1564,471,471,471
BEGIN DESCRIPTION:
Mapping XS 23541dcb
END DESCRIPTION:
XS GIS Cut Line= 4
      1615420.68      6982152.56      1615583.98      6981767.57
      1615618.09      6981578.76      1615494.40      6981093.13
#Sta/Elev= 30
  4581.8 1551.35  4673.7 1550.87  4717.1 1549.29  4810.0 1547.67  4905.4 1547.60
  4939.2 1547.43  4994.2 1545.72  4994.7 1545.22  4999.4 1545.22  4999.8 1545.72
  5031.6 1546.44  5093.1 1546.78  5117.5 1546.36  5141.6 1545.95  5152.0 1546.63
  5162.1 1546.27  5203.0 1546.51  5254.6 1548.04  5344.2 1547.83  5368.1 1549.00
  5390.3 1548.91  5399.0 1549.30  5491.9 1550.03  5522.9 1550.60  5543.5 1551.86
  5572.9 1551.72  5586.1 1552.08  5636.4 1552.89  5677.7 1554.27  5693.0 1554.42
#Mann=8,-1,0
  4581.8   0.035       0  4905.4    0.07       0  4994.2    0.07       0
  4999.8    0.07       0  5031.6   0.035       0  5117.5    0.07       0
  5572.9    0.16       0  5586.1    0.07       0
Bank Sta=4994.2,4999.8
Exp/Cntr=0.3,0.1

Type RM Length L Ch R = 1,1093,150,150,150
BEGIN DESCRIPTION:
Mapping XS 05d235a0
END DESCRIPTION:
XS GIS Cut Line= 3
      1615497.46      6982201.48      1615970.06      6981588.13
      1615988.78      6981234.43
#Sta/Elev= 30
  4225.7 1551.12  4305.7 1550.85  4332.8 1549.64  4382.6 1549.56  4505.0 1547.49
  4554.8 1547.78  4576.0 1547.46  4689.7 1546.94  4710.6 1547.21  4789.4 1545.96
  4810.8 1546.33  4818.4 1545.72  4839.2 1546.12  4853.7 1545.58  4868.2 1545.94
  4903.5 1545.53  4953.4 1546.00  4967.9 1545.74  4988.7 1544.60  5002.6 1544.98
  5007.3 1544.55  5007.8 1544.05  5012.5 1544.05  5013.0 1544.55  5040.2 1545.58
  5070.2 1547.52  5128.7 1550.34  5191.7 1551.81  5250.5 1552.57  5354.2 1553.14
#Mann=5,-1,0
  4225.7   0.035       0  4576.0    0.07       0  5007.3    0.07       0
  5013.0    0.07       0  5128.7    0.16       0
Bank Sta=5007.3,5013
Exp/Cntr=0.3,0.1

Type RM Length L Ch R = 1,943,223,223,223
BEGIN DESCRIPTION:
Mapping XS 6e14830a
END DESCRIPTION:
XS GIS Cut Line= 4
      1615613.57      6982175.60      1616007.61      6981889.75
      1616104.42      6981537.20      1616102.28      6981326.71
#Sta/Elev= 30
  4147.6 1549.25  4218.7 1549.30  4304.5 1547.51  4345.4 1547.36  4433.5 1547.59
  4490.9 1546.71  4541.1 1547.08  4547.3 1546.62  4591.4 1546.78  4689.1 1545.99
  4708.8 1546.24  4716.5 1546.83  4721.7 1545.96  4781.4 1546.00  4802.1 1545.27
  4830.2 1545.52  4835.3 1545.05  4844.3 1545.39  4869.8 1546.01  4937.0 1546.17
  4968.1 1545.07  4980.6 1543.04  4981.1 1542.54  4985.9 1542.54  4986.3 1543.04
  4988.8 1543.67  5002.1 1544.28  5029.2 1548.45  5106.7 1552.41  5210.5 1554.14
#Mann=7,-1,0
  4147.6   0.035       0  4345.4    0.07       0  4689.1   0.035       0
  4844.3    0.07       0  4980.6    0.07       0  4986.3    0.07       0
  5106.7    0.16       0
Bank Sta=4980.6,4986.3
Exp/Cntr=0.3,0.1

Type RM Length L Ch R = 1,720,213,213,213
BEGIN DESCRIPTION:
Mapping XS fd246e3c
END DESCRIPTION:
XS GIS Cut Line= 3
      1616021.15      6981990.02      1616309.66      6981595.96
      1616271.47      6981304.33
#Sta/Elev= 30
  4510.9 1546.36  4537.4 1546.09  4550.6 1546.47  4564.5 1545.86  4614.6 1545.77
  4637.3 1545.23  4655.0 1545.60  4673.3 1545.86  4723.5 1545.31  4759.0 1545.79
  4851.7 1543.78  4870.0 1543.63  4870.4 1543.13  4875.2 1543.13  4875.7 1543.63
  4915.7 1544.68  4922.4 1544.25  4945.0 1544.62  4972.1 1543.76  4980.5 1544.27
  4999.3 1543.65  5037.6 1545.08  5128.3 1545.15  5147.1 1546.52  5158.6 1549.21
  5198.9 1551.85  5231.0 1552.74  5259.4 1552.56  5279.6 1553.16  5293.4 1553.05
#Mann=5,-1,0
  4510.9    0.07       0  4655.0   0.035       0  4851.7    0.07       0
  4870.0    0.07       0  4875.7    0.07       0
Bank Sta=4870,4875.7
Exp/Cntr=0.3,0.1

Type RM Length L Ch R = 1,507,454,454,454
BEGIN DESCRIPTION:
Mapping XS cad82d1c
END DESCRIPTION:
XS GIS Cut Line= 3
      1616109.70      6981928.38      1616492.76      6981678.69
      1617086.17      6981027.58
#Sta/Elev= 30
  4539.6 1545.81  4550.7 1545.30  4597.9 1545.04  4638.2 1544.84  4689.2 1545.40
  4710.7 1545.18  4737.7 1543.68  4780.0 1543.21  4780.5 1542.71  4785.8 1542.71
  4786.3 1543.21  4789.1 1543.81  4825.3 1544.60  4901.1 1544.90  5006.1 1544.29
  5027.0 1543.38  5062.8 1544.08  5105.4 1543.92  5161.5 1544.76  5204.0 1544.75
  5260.8 1546.76  5345.9 1548.53  5366.9 1549.57  5444.6 1549.89  5540.6 1551.14
  5607.4 1551.31  5700.2 1552.48  5834.4 1553.05  5869.6 1553.61  5877.8 1554.19
#Mann=7,-1,0
  4539.6    0.07       0  4597.9   0.035       0  4780.0    0.07       0
  4786.3   0.035       0  4901.1    0.07       0  5540.6   0.035       0
  5700.2    0.07       0
Bank Sta=4780,4786.3
Exp/Cntr=0.3,0.1

Type RM Length L Ch R = 1,53,0,0,0
BEGIN DESCRIPTION:
Chimney Creek 1129 1.0
END DESCRIPTION:
XS GIS Cut Line= 3
      1616105.36      6981946.61      1616799.67      6981985.49
      1616989.68      6981542.20
#Sta/Elev= 30
  4304.6 1545.86  4324.3 1545.37  4391.5 1545.07  4614.7 1543.97  4644.8 1542.75
  4664.8 1542.81  4674.8 1542.37  4694.9 1542.81  4791.7 1543.08  4835.1 1543.31
  4855.1 1542.71  4885.1 1542.98  4905.2 1542.39  4925.2 1542.70  4952.8 1542.40
  4957.8 1542.77  4972.1 1542.24  4972.6 1541.74  4977.9 1541.74  4978.4 1542.24
  5019.0 1542.92  5095.2 1542.94  5312.8 1544.54  5353.5 1545.85  5367.2 1545.54
  5429.7 1547.95  5435.1 1547.56  5453.3 1548.36  5458.7 1548.06  5482.3 1548.49
#Mann=5,-1,0
  4304.6    0.07       0  4391.5   0.035       0  4791.7    0.07       0
  4972.1    0.07       0  4978.4    0.07       0
Bank Sta=4972.1,4978.4
Exp/Cntr=0.3,0.1

Chan Stop Cuts=-1