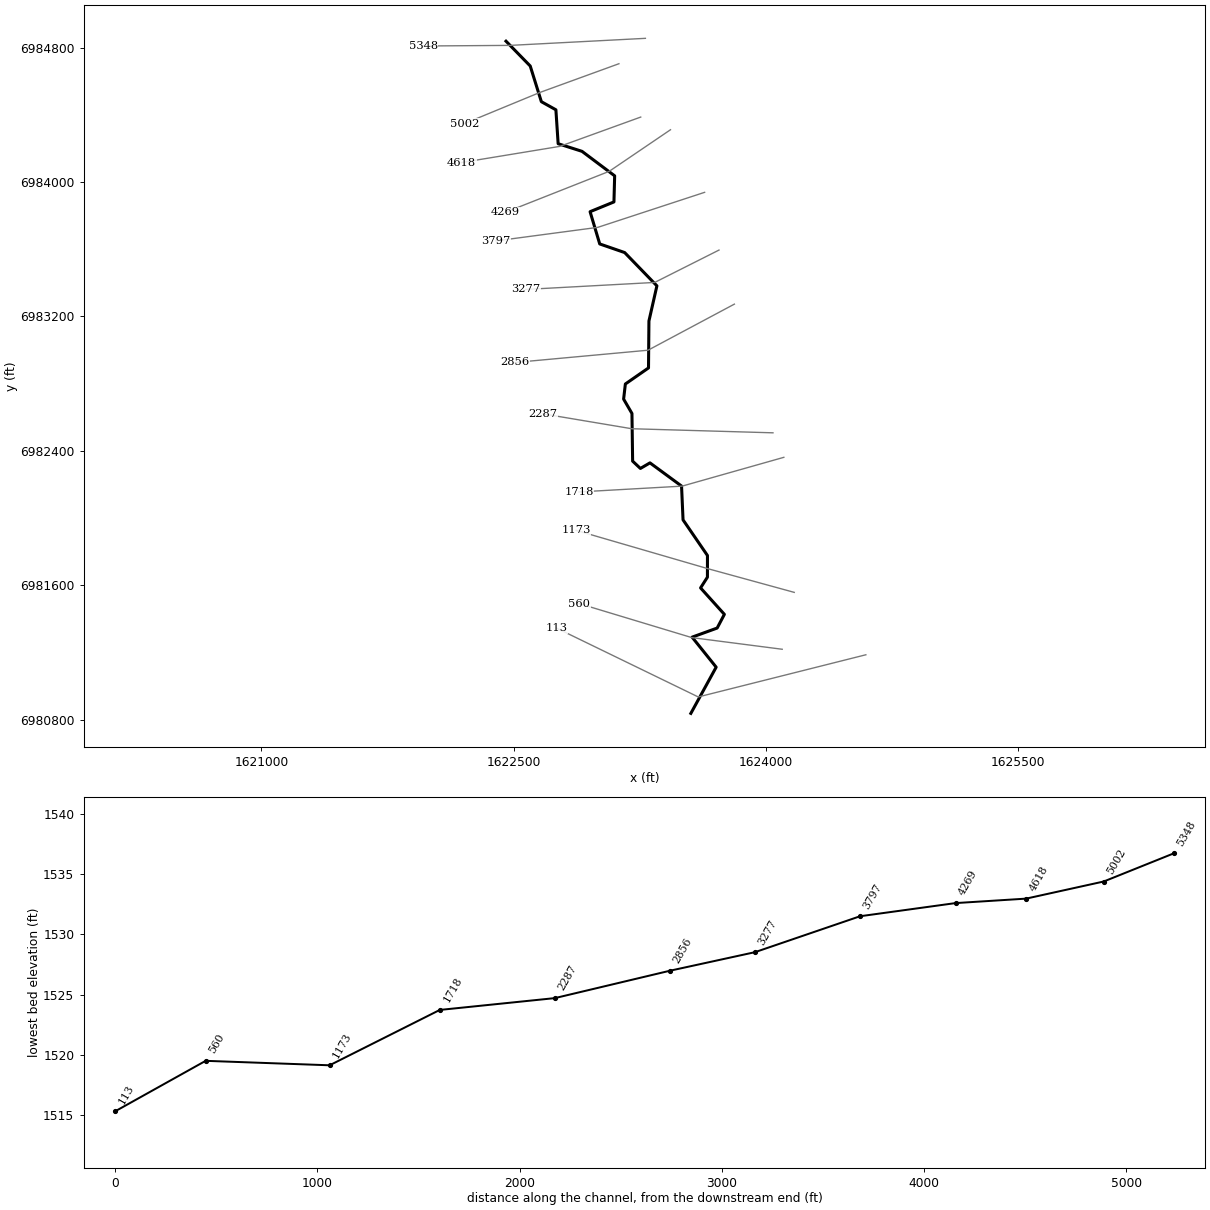
--- Chimney Creek 1130.prj (project) ---

Proj Title=Chimney Creek 1130 Base Level Engineering
Current Plan=p01
Default Exp/Contr=0.3,0.1
English Units
Geom File=g01
Flow File=f01
Plan File=p01
BEGIN DESCRIPTION:
Chimney Creek 1130
END DESCRIPTION:

--- Chimney Creek 1130.p01 (plan) ---

Plan Title=Multiple Run
Short Identifier=Multiple
Geom File=g01
Flow File=f01
Subcritical Flow
K Sum by GR= 0
Std Step Tol= 0.01
Critical Tol= 0.01
Num of Std Step Trials= 20
Max Error Tol= 0.3
Flow Tol Ratio= 0.001
Split Flow NTrial= 30
Split Flow Tol= 0.02
Split Flow Ratio= 0.02
Log Output Level= 0
Friction Slope Method= 1
Unsteady Friction Slope Method= 2
Unsteady Bridges Friction Slope Method= 1
Parabolic Critical Depth
Global Vel Dist=  1 , 1 , 1
Global Log Level= 0
CheckData=True
Encroach Param= -1, 0, 0, 0
BEGIN DESCRIPTION:
Multiple Run
END DESCRIPTION:

--- Chimney Creek 1130.f01 (steady flow) ---

Flow Title=Multiple
Number of Profiles=7
Profile Names=10-year,25-year,50-year,1pct_min,100-year,1pct_plu,500-year
River Rch & RM= Chimney Creek 11,Reach-1,5348
     282     389     476     290     579    1156     868
Boundary for River Rch & Prof#=Chimney Creek 11,Reach-1,1
Up Type=0
Dn Type=3
Dn Slope=0.005
Boundary for River Rch & Prof#=Chimney Creek 11,Reach-1,2
Up Type=0
Dn Type=3
Dn Slope=0.005
Boundary for River Rch & Prof#=Chimney Creek 11,Reach-1,3
Up Type=0
Dn Type=3
Dn Slope=0.005
Boundary for River Rch & Prof#=Chimney Creek 11,Reach-1,4
Up Type=0
Dn Type=3
Dn Slope=0.005
Boundary for River Rch & Prof#=Chimney Creek 11,Reach-1,5
Up Type=0
Dn Type=3
Dn Slope=0.005
Boundary for River Rch & Prof#=Chimney Creek 11,Reach-1,6
Up Type=0
Dn Type=3
Dn Slope=0.005
Boundary for River Rch & Prof#=Chimney Creek 11,Reach-1,7
Up Type=0
Dn Type=3
Dn Slope=0.005

--- Chimney Creek 1130.g01 (geometry) ---

Geom Title=Existing Conditions

River Reach=Chimney Creek 11,Reach-1
Reach XY= 30
      1622455.00      6984838.00      1622599.17      6984690.30
      1622665.44      6984477.92      1622751.90      6984429.69
      1622765.32      6984227.83      1622907.42      6984182.46
      1623101.56      6984036.75      1623097.33      6983881.48
      1622955.34      6983823.38      1623012.73      6983631.50
      1623161.17      6983580.14      1623352.95      6983382.14
      1623305.52      6983172.78      1623303.02      6982893.67
      1623165.30      6982798.10      1623154.89      6982708.11
      1623204.48      6982622.78      1623208.54      6982339.00
      1623254.75      6982295.46      1623311.65      6982328.68
      1623499.64      6982190.70      1623508.55      6981989.47
      1623653.81      6981777.50      1623653.62      6981648.44
      1623612.80      6981584.58      1623754.47      6981427.31
      1623711.55      6981345.75      1623562.47      6981291.62
      1623705.59      6981113.00      1623555.00      6980838.00

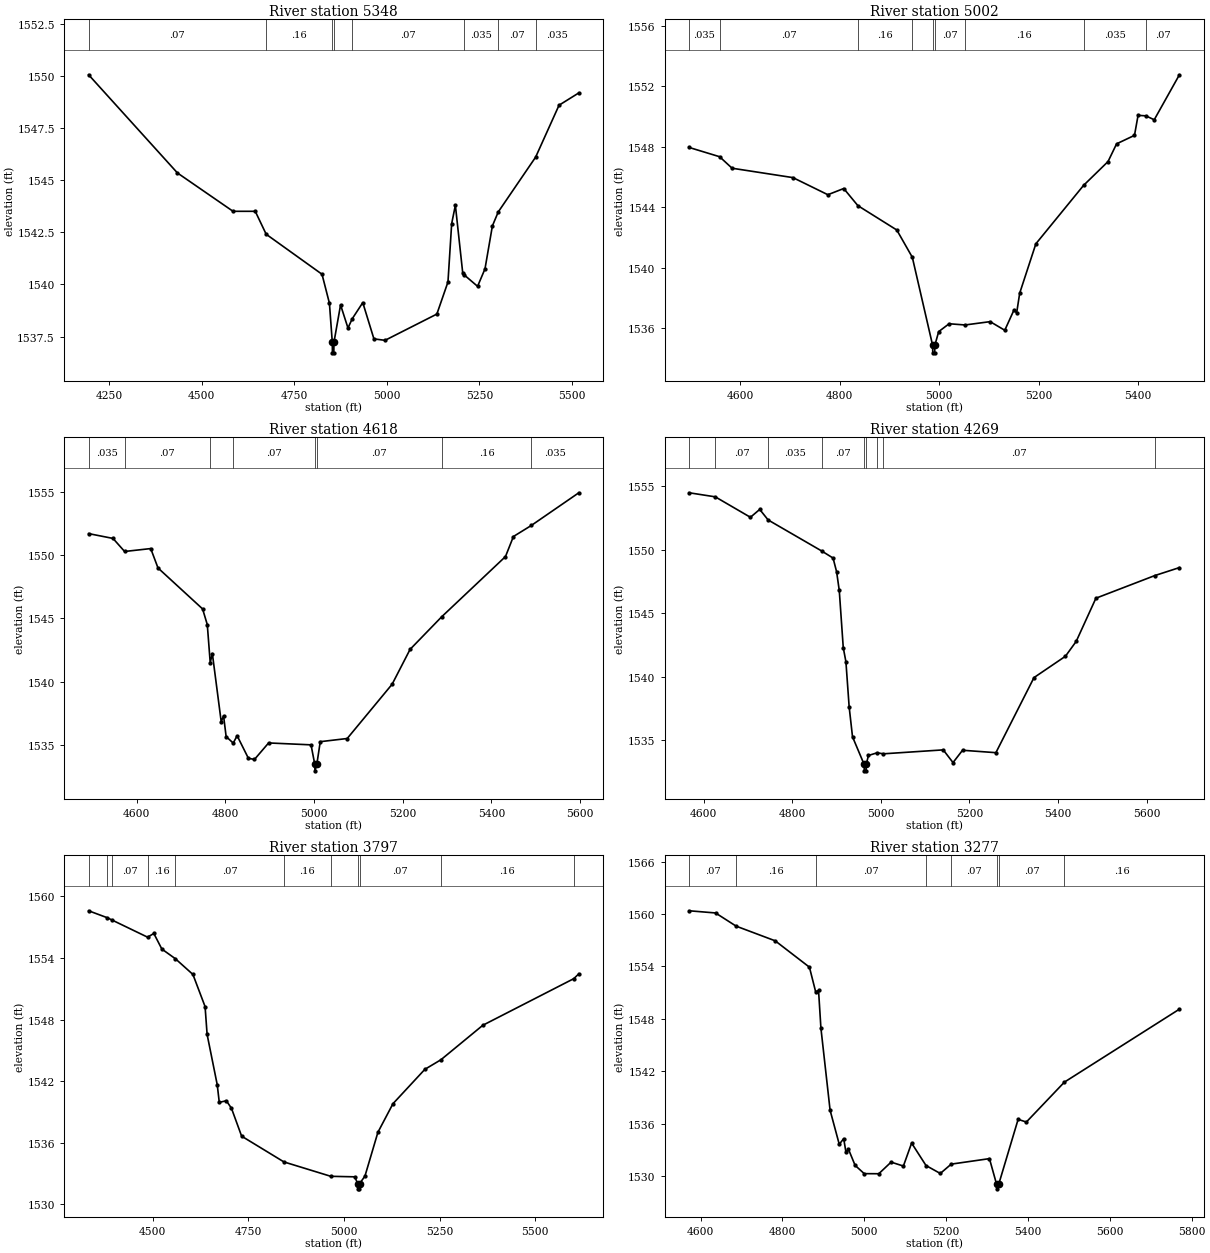
Type RM Length L Ch R = 1,5348,346,346,346
BEGIN DESCRIPTION:
Chimney Creek 1130 11.0
END DESCRIPTION:
XS GIS Cut Line= 3
      1623284.53      6984854.95      1622480.00      6984813.00
      1621961.64      6984809.38
#Sta/Elev= 30
  4194.4 1550.06  4434.3 1545.35  4584.5 1543.51  4644.5 1543.51  4674.0 1542.41
  4824.8 1540.49  4844.8 1539.10  4852.6 1537.22  4852.9 1536.72  4856.7 1536.72
  4857.0 1537.22  4874.9 1539.02  4894.9 1537.91  4906.6 1538.36  4934.9 1539.13
  4965.0 1537.39  4995.0 1537.32  5135.0 1538.58  5165.0 1540.12  5175.0 1542.92
  5185.0 1543.80  5205.0 1540.53  5209.4 1540.45  5245.0 1539.91  5265.0 1540.75
  5285.0 1542.81  5300.8 1543.48  5401.8 1546.11  5465.0 1548.60  5518.4 1549.19
#Mann=8,-1,0
  4194.4    0.07       0  4674.0    0.16       0  4852.6    0.07       0
  4857.0    0.16       0  4906.6    0.07       0  5209.4   0.035       0
  5300.8    0.07       0  5401.8   0.035       0
Bank Sta=4852.6,4857
Exp/Cntr=0.3,0.1

Type RM Length L Ch R = 1,5002,384,384,384
BEGIN DESCRIPTION:
Mapping XS babede7f
END DESCRIPTION:
XS GIS Cut Line= 3
      1623127.02      6984703.92      1622654.34      6984532.04
      1622208.22      6984347.88
#Sta/Elev= 30
  4497.6 1547.95  4558.7 1547.34  4583.8 1546.58  4706.2 1545.96  4776.4 1544.83
  4808.3 1545.24  4836.7 1544.11  4915.0 1542.50  4946.2 1540.70  4987.0 1534.89
  4987.3 1534.39  4991.2 1534.39  4991.5 1534.89  4999.2 1535.79  5020.2 1536.31
  5052.3 1536.23  5102.7 1536.45  5132.1 1535.88  5150.6 1537.22  5156.0 1537.03
  5162.1 1538.33  5194.6 1541.59  5290.6 1545.45  5339.7 1547.02  5356.9 1548.19
  5392.9 1548.75  5400.1 1550.07  5415.6 1550.04  5432.6 1549.78  5483.2 1552.75
#Mann=9,-1,0
  4497.6   0.035       0  4558.7    0.07       0  4836.7    0.16       0
  4946.2    0.07       0  4987.0    0.07       0  4991.5    0.07       0
  5052.3    0.16       0  5290.6   0.035       0  5415.6    0.07       0
Bank Sta=4987,4991.5
Exp/Cntr=0.3,0.1

Type RM Length L Ch R = 1,4618,349,349,349
BEGIN DESCRIPTION:
Mapping XS 613c7f36
END DESCRIPTION:
XS GIS Cut Line= 3
      1623256.70      6984386.47      1622774.91      6984211.99
      1622189.49      6984115.72
#Sta/Elev= 30
  4491.3 1551.68  4546.3 1551.30  4572.5 1550.27  4631.4 1550.50  4647.8 1548.97
  4748.4 1545.74  4759.0 1544.50  4765.6 1541.50  4770.4 1542.22  4790.4 1536.84
  4795.7 1537.31  4801.5 1535.67  4817.5 1535.16  4826.3 1535.74  4851.7 1533.96
  4865.4 1533.87  4897.3 1535.17  4993.0 1535.02  5001.5 1533.47  5001.8 1532.97
  5006.0 1533.47  5013.8 1535.27  5074.6 1535.52  5175.9 1539.80  5216.4 1542.55
  5287.7 1545.12  5431.6 1549.87  5449.5 1551.45  5489.8 1552.32  5597.0 1554.90
#Mann=8,-1,0
  4491.3   0.035       0  4572.5    0.07       0  4765.6    0.16       0
  4817.5    0.07       0  5001.5    0.07       0  5006.0    0.07       0
  5287.7    0.16       0  5489.8   0.035       0
Bank Sta=5001.5,5006
Exp/Cntr=0.3,0.1

Type RM Length L Ch R = 1,4269,472,472,472
BEGIN DESCRIPTION:
Mapping XS 866c4499
END DESCRIPTION:
XS GIS Cut Line= 3
      1623433.78      6984310.96      1623069.18      6984063.55
      1622449.67      6983818.87
#Sta/Elev= 30
  4567.5 1554.49  4626.4 1554.17  4705.7 1552.56  4726.7 1553.18  4745.7 1552.35
  4866.5 1549.91  4892.3 1549.35  4900.3 1548.27  4906.3 1546.80  4915.3 1542.30
  4921.3 1541.19  4928.6 1537.64  4936.2 1535.28  4962.5 1533.10  4962.9 1532.60
  4966.8 1532.60  4967.1 1533.10  4972.2 1533.81  4991.8 1534.02  5005.8 1533.94
  5141.0 1534.25  5163.1 1533.25  5184.6 1534.22  5259.9 1534.03  5345.9 1539.94
  5416.9 1541.62  5441.2 1542.79  5485.7 1546.19  5618.5 1547.97  5674.2 1548.60
#Mann=9,-1,0
  4567.5   0.035       0  4626.4    0.07       0  4745.7   0.035       0
  4866.5    0.07       0  4962.5   0.035       0  4967.1    0.07       0
  4991.8   0.035       0  5005.8    0.07       0  5618.5    0.16       0
Bank Sta=4962.5,4967.1
Exp/Cntr=0.3,0.1

Type RM Length L Ch R = 1,3797,520,520,520
BEGIN DESCRIPTION:
Mapping XS bd97a53f
END DESCRIPTION:
XS GIS Cut Line= 3
      1623636.90      6983938.55      1623001.47      6983730.22
      1622394.73      6983649.49
#Sta/Elev= 30
  4332.8 1558.59  4381.8 1557.91  4393.3 1557.70  4486.8 1556.02  4503.2 1556.38
  4524.2 1554.86  4559.5 1553.92  4605.3 1552.39  4637.1 1549.26  4642.4 1546.55
  4668.9 1541.64  4674.2 1539.93  4692.6 1540.09  4706.0 1539.36  4732.6 1536.64
  4843.2 1534.13  4965.6 1532.73  5028.2 1532.68  5035.9 1532.01  5036.3 1531.51
  5040.4 1531.51  5040.7 1532.01  5054.8 1532.75  5088.7 1537.02  5128.0 1539.80
  5211.4 1543.15  5253.3 1544.08  5362.8 1547.44  5600.5 1551.98  5613.6 1552.45
#Mann=11,-1,0
  4332.8    0.07       0  4381.8   0.035       0  4393.3    0.07       0
  4486.8    0.16       0  4559.5    0.07       0  4843.2    0.16       0
  4965.6    0.07       0  5035.9    0.07       0  5040.7    0.07       0
  5253.3    0.16       0  5600.5    0.07       0
Bank Sta=5035.9,5040.7
Exp/Cntr=0.3,0.1

Type RM Length L Ch R = 1,3277,421,421,421
BEGIN DESCRIPTION:
Mapping XS 37749a3a
END DESCRIPTION:
XS GIS Cut Line= 3
      1623722.53      6983595.04      1623339.76      6983402.35
      1622571.53      6983360.68
#Sta/Elev= 30
  4572.2 1560.38  4636.6 1560.13  4686.9 1558.62  4782.3 1556.94  4866.0 1553.92
  4881.2 1551.10  4888.3 1551.25  4894.1 1546.92  4916.5 1537.53  4938.9 1533.63
  4949.7 1534.28  4955.3 1532.72  4961.3 1533.08  4977.6 1531.22  4999.9 1530.27
  5035.5 1530.26  5065.6 1531.59  5095.6 1531.14  5115.7 1533.77  5150.9 1531.20
  5185.8 1530.29  5212.5 1531.36  5305.9 1531.99  5323.5 1529.03  5323.9 1528.53
  5328.4 1529.03  5376.0 1536.49  5396.1 1536.18  5489.0 1540.75  5770.1 1549.11
#Mann=8,-1,0
  4572.2    0.07       0  4686.9    0.16       0  4881.2    0.07       0
  5150.9    0.16       0  5212.5    0.07       0  5323.5    0.07       0
  5328.4    0.07       0  5489.0    0.16       0
Bank Sta=5323.5,5328.4
Exp/Cntr=0.3,0.1

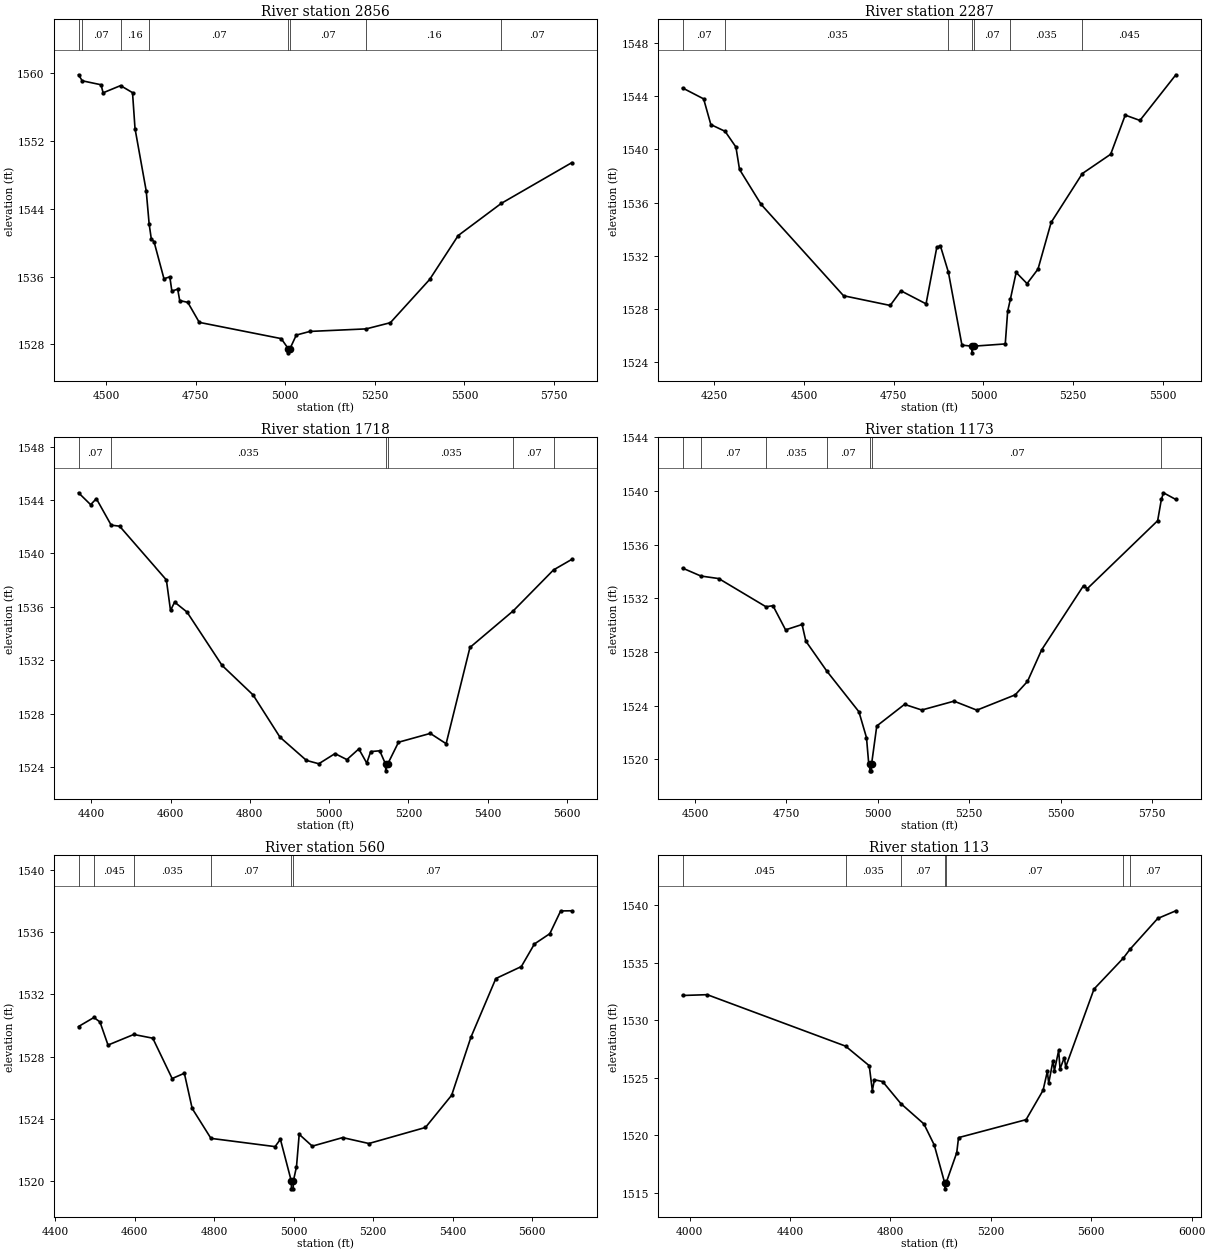
Type RM Length L Ch R = 1,2856,569,569,569
BEGIN DESCRIPTION:
Mapping XS ca54a8ea
END DESCRIPTION:
XS GIS Cut Line= 3
      1623814.09      6983273.37      1623300.17      6982999.05
      1622509.27      6982926.21
#Sta/Elev= 30
  4423.0 1559.84  4433.3 1559.13  4485.9 1558.66  4491.6 1557.71  4540.3 1558.56
  4573.7 1557.73  4580.7 1553.48  4612.0 1546.10  4620.1 1542.22  4626.0 1540.48
  4633.9 1540.10  4661.5 1535.74  4677.8 1535.97  4683.5 1534.29  4699.8 1534.51
  4705.4 1533.17  4728.0 1532.95  4760.0 1530.59  4988.7 1528.67  5008.3 1527.49
  5008.6 1526.99  5013.2 1527.49  5030.8 1529.09  5068.8 1529.52  5225.8 1529.82
  5293.3 1530.55  5403.0 1535.66  5482.7 1540.85  5603.0 1544.65  5799.8 1549.46
#Mann=8,-1,0
  4423.0   0.035       0  4433.3    0.07       0  4540.3    0.16       0
  4620.1    0.07       0  5008.3    0.07       0  5013.2    0.07       0
  5225.8    0.16       0  5603.0    0.07       0
Bank Sta=5008.3,5013.2
Exp/Cntr=0.3,0.1

Type RM Length L Ch R = 1,2287,569,569,569
BEGIN DESCRIPTION:
Mapping XS 7523d35c
END DESCRIPTION:
XS GIS Cut Line= 3
      1624043.82      6982507.50      1623203.53      6982531.81
      1622675.75      6982620.35
#Sta/Elev= 30
  4160.9 1544.62  4219.7 1543.80  4239.8 1541.87  4279.6 1541.36  4309.8 1540.18
  4319.8 1538.50  4379.8 1535.88  4609.9 1529.01  4740.0 1528.28  4770.0 1529.38
  4840.0 1528.40  4870.0 1532.65  4880.0 1532.76  4902.3 1530.78  4940.1 1525.30
  4967.5 1525.22  4967.9 1524.72  4972.6 1525.22  5060.9 1525.39  5067.6 1527.84
  5075.5 1528.79  5091.3 1530.76  5121.7 1529.92  5152.2 1531.01  5188.9 1534.52
  5275.9 1538.19  5354.9 1539.64  5395.5 1542.58  5436.5 1542.18  5536.7 1545.61
#Mann=7,-1,0
  4160.9    0.07       0  4279.6   0.035       0  4902.3    0.07       0
  4967.5    0.07       0  4972.6    0.07       0  5075.5   0.035       0
  5275.9   0.045       0
Bank Sta=4967.5,4972.6
Exp/Cntr=0.3,0.1

Type RM Length L Ch R = 1,1718,545,545,545
BEGIN DESCRIPTION:
Mapping XS 902fdc7f
END DESCRIPTION:
XS GIS Cut Line= 3
      1624108.34      6982361.67      1623502.86      6982190.23
      1622888.32      6982155.60
#Sta/Elev= 30
  4367.8 1544.54  4398.4 1543.65  4412.8 1544.10  4450.2 1542.12  4471.5 1542.04
  4589.5 1538.02  4599.9 1535.74  4610.3 1536.36  4641.5 1535.62  4729.9 1531.63
  4808.2 1529.42  4876.1 1526.26  4942.9 1524.52  4974.1 1524.27  5015.0 1525.03
  5045.0 1524.58  5075.1 1525.38  5095.1 1524.32  5105.1 1525.18  5127.9 1525.24
  5142.6 1524.24  5143.0 1523.74  5147.8 1524.24  5175.2 1525.88  5255.4 1526.54
  5295.4 1525.77  5355.5 1532.97  5465.2 1535.72  5566.4 1538.77  5612.6 1539.56
#Mann=6,-1,0
  4367.8    0.07       0  4450.2   0.035       0  5142.6   0.035       0
  5147.8   0.035       0  5465.2    0.07       0  5566.4   0.045       0
Bank Sta=5142.6,5147.8
Exp/Cntr=0.3,0.1

Type RM Length L Ch R = 1,1173,613,613,613
BEGIN DESCRIPTION:
Mapping XS ec873da3
END DESCRIPTION:
XS GIS Cut Line= 3
      1624170.22      6981558.06      1623655.86      6981699.12
      1622872.47      6981926.98
#Sta/Elev= 30
  4466.2 1534.25  4516.3 1533.66  4565.3 1533.47  4694.4 1531.37  4713.5 1531.45
  4748.0 1529.65  4793.1 1530.05  4803.4 1528.81  4861.0 1526.57  4948.6 1523.55
  4969.3 1521.62  4975.5 1519.65  4978.0 1519.65  4978.4 1519.15  4982.8 1519.15
  4983.2 1519.65  4997.4 1522.49  5073.3 1524.10  5120.5 1523.68  5208.7 1524.34
  5271.2 1523.67  5376.0 1524.81  5409.6 1525.81  5448.3 1528.16  5562.8 1532.94
  5573.2 1532.72  5765.6 1537.78  5775.7 1539.36  5781.5 1539.86  5815.4 1539.36
#Mann=7,-1,0
  4466.2   0.045       0  4516.3    0.07       0  4694.4   0.035       0
  4861.0    0.07       0  4978.0    0.07       0  4983.2    0.07       0
  5775.7   0.045       0
Bank Sta=4978,4983.2
Exp/Cntr=0.3,0.1

Type RM Length L Ch R = 1,560,447,447,447
BEGIN DESCRIPTION:
Mapping XS 138675ba
END DESCRIPTION:
XS GIS Cut Line= 3
      1624098.60      6981219.52      1623560.37      6981288.97
      1622891.97      6981490.79
#Sta/Elev= 30
  4459.0 1529.94  4497.8 1530.52  4513.0 1530.23  4533.2 1528.75  4598.0 1529.43
  4645.8 1529.19  4694.5 1526.60  4725.2 1526.94  4744.9 1524.68  4792.1 1522.76
  4953.4 1522.23  4966.8 1522.70  4994.2 1520.02  4994.6 1519.52  4999.0 1519.52
  4999.4 1520.02  5007.3 1520.94  5014.1 1523.02  5047.0 1522.26  5123.4 1522.81
  5189.4 1522.43  5331.7 1523.46  5397.6 1525.53  5446.0 1529.25  5508.7 1533.02
  5572.9 1533.79  5605.8 1535.24  5644.5 1535.90  5671.8 1537.36  5699.9 1537.37
#Mann=6,-1,0
  4459.0    0.07       0  4497.8   0.045       0  4598.0   0.035       0
  4792.1    0.07       0  4994.2    0.07       0  4999.4    0.07       0
Bank Sta=4994.2,4999.4
Exp/Cntr=0.3,0.1

Type RM Length L Ch R = 1,113,0,0,0
BEGIN DESCRIPTION:
Chimney Creek 1130 2.0
END DESCRIPTION:
XS GIS Cut Line= 3
      1624596.43      6981186.76      1623599.03      6980935.76
      1622756.10      6981345.18
#Sta/Elev= 30
  3971.5 1532.14  4069.9 1532.21  4621.0 1527.74  4715.4 1526.04  4727.7 1523.88
  4736.0 1524.82  4768.8 1524.66  4841.2 1522.75  4933.2 1520.98  4974.4 1519.15
  5016.2 1515.84  5016.7 1515.34  5021.5 1515.84  5064.0 1518.48  5071.2 1519.79
  5340.3 1521.35  5408.0 1523.90  5425.0 1525.54  5430.5 1524.52  5447.5 1526.47
  5453.1 1525.60  5470.1 1527.36  5475.6 1525.77  5492.6 1526.74  5498.2 1525.93
  5611.0 1532.70  5727.9 1535.39  5754.2 1536.15  5864.7 1538.83  5937.1 1539.50
#Mann=7,-1,0
  3971.5   0.045       0  4621.0   0.035       0  4841.2    0.07       0
  5016.2    0.07       0  5021.5    0.07       0  5727.9   0.035       0
  5754.2    0.07       0
Bank Sta=5016.2,5021.5
Exp/Cntr=0.3,0.1

Chan Stop Cuts=-1