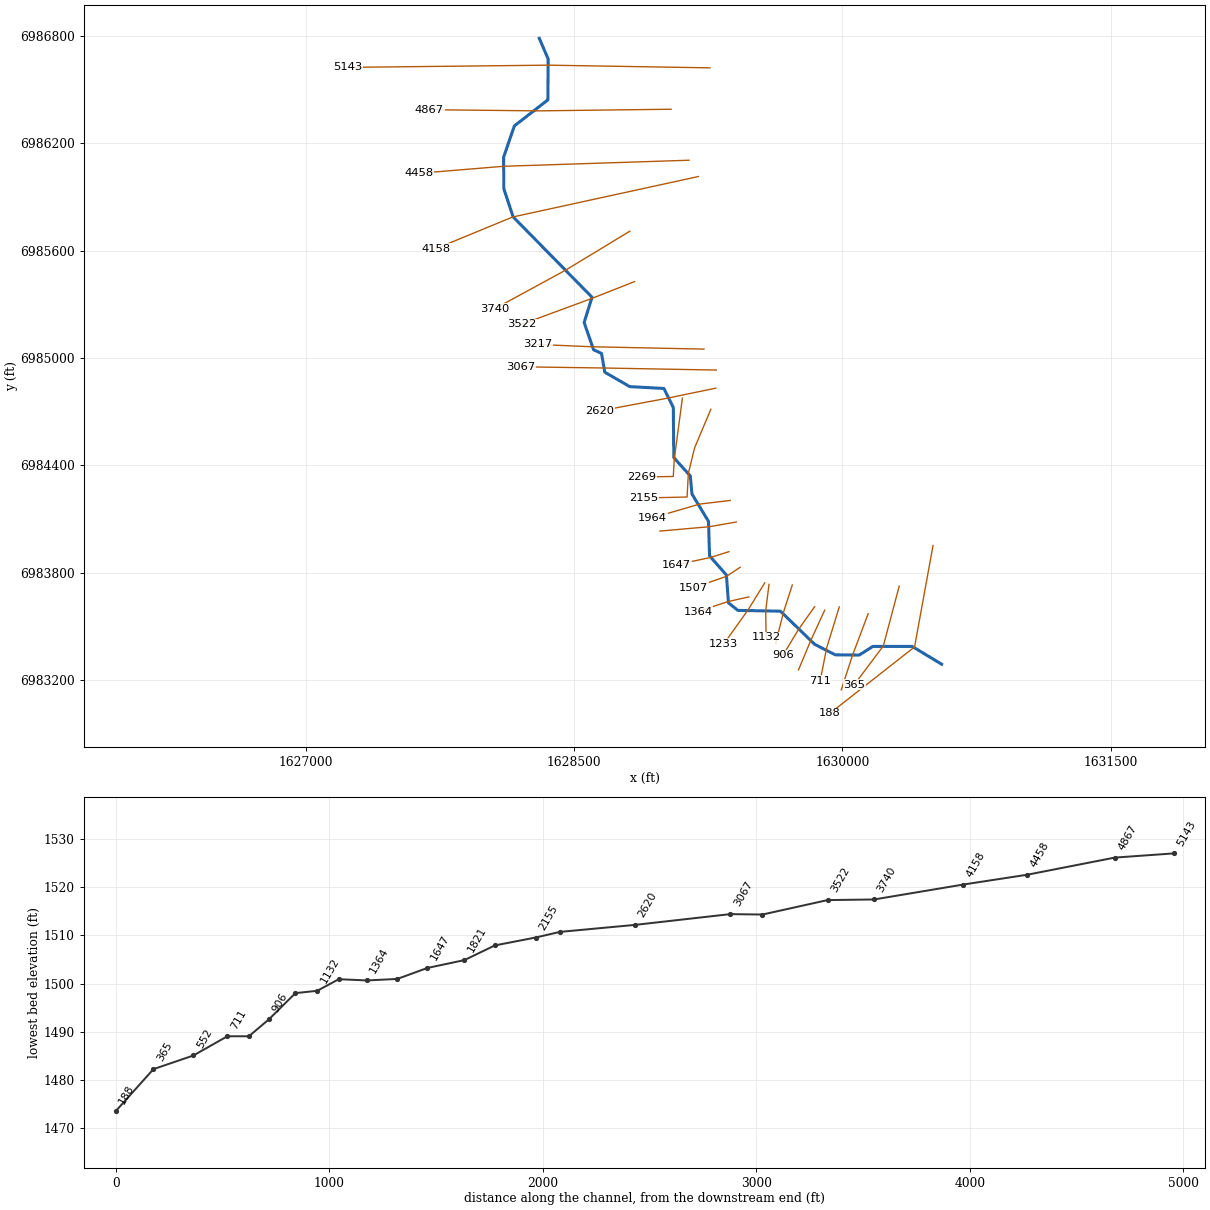
--- Chimney Creek 1131.prj (project) ---

Proj Title=Chimney Creek 1131 Base Level Engineering
Current Plan=p01
Default Exp/Contr=0.3,0.1
English Units
Geom File=g01
Flow File=f01
Plan File=p01
BEGIN DESCRIPTION:
Chimney Creek 1131
END DESCRIPTION:

--- Chimney Creek 1131.p01 (plan) ---

Plan Title=Multiple Run
Short Identifier=Multiple
Geom File=g01
Flow File=f01
Subcritical Flow
K Sum by GR= 0
Std Step Tol= 0.01
Critical Tol= 0.01
Num of Std Step Trials= 20
Max Error Tol= 0.3
Flow Tol Ratio= 0.001
Split Flow NTrial= 30
Split Flow Tol= 0.02
Split Flow Ratio= 0.02
Log Output Level= 0
Friction Slope Method= 1
Unsteady Friction Slope Method= 2
Unsteady Bridges Friction Slope Method= 1
Parabolic Critical Depth
Global Vel Dist=  1 , 1 , 1
Global Log Level= 0
CheckData=True
Encroach Param= -1, 0, 0, 0
BEGIN DESCRIPTION:
Multiple Run
END DESCRIPTION:

--- Chimney Creek 1131.f01 (steady flow) ---

Flow Title=Multiple
Number of Profiles=7
Profile Names=10-year,25-year,50-year,1pct_min,100-year,1pct_plu,500-year
River Rch & RM= Chimney Creek 11,Reach-1,5143
     265     365     446     271     542    1081     809
River Rch & RM= Chimney Creek 11,Reach-1,3067
     300     415     510     312     623    1243     939
River Rch & RM= Chimney Creek 11,Reach-1,1364
     369     517     641     395     789    1574    1210
Boundary for River Rch & Prof#=Chimney Creek 11,Reach-1,1
Up Type=0
Dn Type=3
Dn Slope=0.005
Boundary for River Rch & Prof#=Chimney Creek 11,Reach-1,2
Up Type=0
Dn Type=3
Dn Slope=0.005
Boundary for River Rch & Prof#=Chimney Creek 11,Reach-1,3
Up Type=0
Dn Type=3
Dn Slope=0.005
Boundary for River Rch & Prof#=Chimney Creek 11,Reach-1,4
Up Type=0
Dn Type=3
Dn Slope=0.005
Boundary for River Rch & Prof#=Chimney Creek 11,Reach-1,5
Up Type=0
Dn Type=3
Dn Slope=0.005
Boundary for River Rch & Prof#=Chimney Creek 11,Reach-1,6
Up Type=0
Dn Type=3
Dn Slope=0.005
Boundary for River Rch & Prof#=Chimney Creek 11,Reach-1,7
Up Type=0
Dn Type=3
Dn Slope=0.005

--- Chimney Creek 1131.g01 (geometry) ---

Geom Title=Existing Conditions

River Reach=Chimney Creek 11,Reach-1
Reach XY= 30
      1628305.00      6986788.00      1628354.55      6986672.81
      1628352.95      6986443.84      1628165.39      6986298.10
      1628105.68      6986124.08      1628106.22      6985948.50
      1628158.61      6985789.50      1628599.91      6985340.30
      1628555.77      6985198.69      1628608.55      6985046.50
      1628652.92      6985025.98      1628671.31      6984920.89
      1628810.52      6984840.35      1629001.65      6984829.91
      1629054.34      6984724.10      1629057.18      6984443.45
      1629149.46      6984340.42      1629158.83      6984239.59
      1629251.25      6984086.45      1629257.07      6983893.86
      1629351.44      6983786.53      1629362.68      6983631.48
      1629415.26      6983588.98      1629653.54      6983584.46
      1629845.32      6983398.76      1629960.52      6983340.34
      1630094.49      6983339.21      1630170.22      6983387.48
      1630389.84      6983387.62      1630555.00      6983288.00

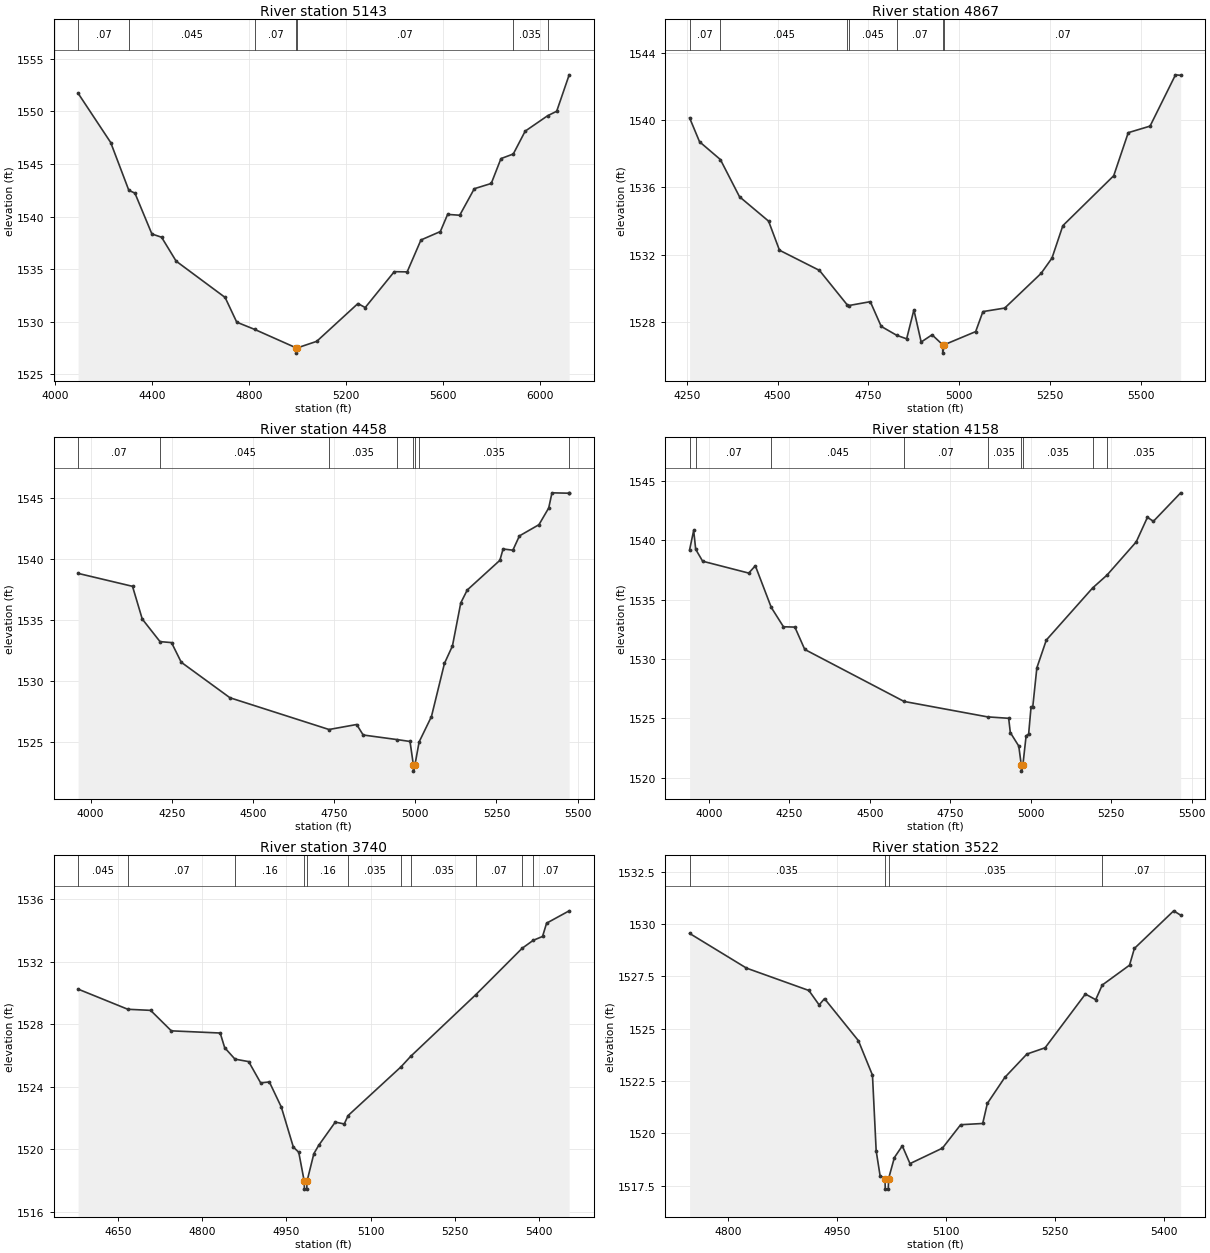
Type RM Length L Ch R = 1,5143,276,276,276
BEGIN DESCRIPTION:
Chimney Creek 1131 11.0
END DESCRIPTION:
XS GIS Cut Line= 3
      1629259.48      6986622.97      1628355.00      6986638.00
      1627233.47      6986625.58
#Sta/Elev= 30
  4095.8 1551.71  4230.3 1547.03  4305.1 1542.49  4330.3 1542.22  4400.3 1538.34
  4440.3 1538.03  4500.3 1535.76  4702.4 1532.31  4750.4 1529.96  4824.7 1529.27
  4995.6 1527.52  4995.9 1527.02  5000.2 1527.52  5080.4 1528.14  5250.4 1531.73
  5280.4 1531.35  5400.4 1534.76  5453.6 1534.74  5510.4 1537.77  5590.4 1538.57
  5620.4 1540.20  5670.4 1540.12  5730.5 1542.64  5800.5 1543.14  5840.5 1545.50
  5891.4 1545.94  5940.5 1548.11  6032.8 1549.57  6070.5 1550.00  6122.0 1553.46
#Mann=7,-1,0
  4095.8    0.07       0  4305.1   0.045       0  4824.7    0.07       0
  4995.6    0.07       0  5000.2    0.07       0  5891.4   0.035       0
  6032.8    0.07       0
Bank Sta=4995.6,5000.2
Exp/Cntr=0.3,0.1

Type RM Length L Ch R = 1,4867,409,409,409
BEGIN DESCRIPTION:
Mapping XS 7ec347c6
END DESCRIPTION:
XS GIS Cut Line= 3
      1629042.35      6986391.51      1628297.51      6986382.39
      1627690.74      6986388.90
#Sta/Elev= 30
  4257.7 1540.14  4285.1 1538.72  4342.5 1537.66  4395.1 1535.45  4475.1 1534.00
  4505.1 1532.27  4615.1 1531.07  4691.2 1529.03  4696.0 1528.98  4755.1 1529.21
  4785.1 1527.74  4827.8 1527.21  4855.1 1527.00  4875.1 1528.72  4895.1 1526.81
  4925.1 1527.24  4954.2 1526.65  4954.5 1526.15  4958.9 1526.65  5045.1 1527.43
  5065.1 1528.62  5125.1 1528.83  5225.1 1530.89  5255.1 1531.80  5285.1 1533.73
  5425.1 1536.70  5465.1 1539.26  5525.1 1539.65  5595.1 1542.70  5609.4 1542.67
#Mann=7,-1,0
  4257.7    0.07       0  4342.5   0.045       0  4691.2    0.07       0
  4696.0   0.045       0  4827.8    0.07       0  4954.2    0.07       0
  4958.9    0.07       0
Bank Sta=4954.2,4958.9
Exp/Cntr=0.3,0.1

Type RM Length L Ch R = 1,4458,300,300,300
BEGIN DESCRIPTION:
Mapping XS 011cef91
END DESCRIPTION:
XS GIS Cut Line= 3
      1629142.53      6986106.35      1628106.10      6986072.50
      1627632.19      6986033.44
#Sta/Elev= 30
  3961.6 1538.80  4129.2 1537.74  4159.2 1535.06  4213.9 1533.21  4249.3 1533.13
  4279.3 1531.52  4429.4 1528.61  4734.4 1526.01  4819.6 1526.42  4839.6 1525.56
  4942.6 1525.19  4983.9 1525.03  4994.3 1523.10  4994.6 1522.60  4999.0 1523.10
  5011.9 1524.99  5049.9 1527.07  5090.0 1531.43  5114.6 1532.86  5140.2 1536.38
  5160.2 1537.44  5260.6 1539.87  5270.6 1540.80  5300.7 1540.70  5320.8 1541.87
  5381.0 1542.79  5411.1 1544.16  5421.1 1545.40  5472.1 1545.37  5474.1 1545.37
#Mann=8,-1,0
  3961.6    0.07       0  4213.9   0.045       0  4734.4   0.035       0
  4942.6    0.07       0  4994.3    0.07       0  4999.0    0.07       0
  5011.9   0.035       0  5472.1    0.07       0
Bank Sta=4994.3,4999
Exp/Cntr=0.3,0.1

Type RM Length L Ch R = 1,4158,418,418,418
BEGIN DESCRIPTION:
Mapping XS 27c69287
END DESCRIPTION:
XS GIS Cut Line= 3
      1629194.66      6986015.21      1628155.58      6985788.64
      1627727.68      6985612.30
#Sta/Elev= 30
  3939.7 1539.20  3952.4 1540.83  3958.7 1539.24  3980.3 1538.24  4123.6 1537.24
  4144.0 1537.86  4193.5 1534.35  4231.4 1532.72  4266.9 1532.69  4297.6 1530.81
  4606.2 1526.43  4865.6 1525.13  4931.4 1525.01  4936.5 1523.81  4962.8 1522.67
  4970.7 1521.06  4971.0 1520.56  4975.5 1521.06  4985.6 1523.53  4993.5 1523.69
  5000.9 1525.95  5006.2 1525.95  5019.0 1529.26  5048.4 1531.60  5192.4 1535.99
  5237.0 1537.07  5327.9 1539.87  5362.7 1541.94  5381.2 1541.60  5466.0 1544.00
#Mann=9,-1,0
  3939.7   0.045       0  3958.7    0.07       0  4193.5   0.045       0
  4606.2    0.07       0  4865.6   0.035       0  4970.7   0.035       0
  4975.5   0.035       0  5192.4    0.07       0  5237.0   0.035       0
Bank Sta=4970.7,4975.5
Exp/Cntr=0.3,0.1

Type RM Length L Ch R = 1,3740,218,218,218
BEGIN DESCRIPTION:
Mapping XS 65db2c02
END DESCRIPTION:
XS GIS Cut Line= 3
      1628811.24      6985709.40      1628450.55      6985490.64
      1628053.40      6985274.49
#Sta/Elev= 30
  4579.5 1530.26  4668.0 1528.97  4708.6 1528.90  4745.4 1527.59  4832.4 1527.45
  4840.4 1526.51  4858.7 1525.78  4883.1 1525.62  4904.4 1524.26  4919.9 1524.32
  4941.2 1522.71  4962.6 1520.15  4972.2 1519.82  4982.0 1517.96  4982.3 1517.46
  4986.5 1517.46  4986.9 1517.96  4999.1 1519.73  5007.7 1520.26  5037.2 1521.75
  5053.2 1521.63  5060.1 1522.17  5154.3 1525.29  5171.2 1525.95  5287.5 1529.91
  5369.7 1532.87  5389.4 1533.38  5406.1 1533.63  5413.3 1534.48  5453.5 1535.27
#Mann=11,-1,0
  4579.5   0.045       0  4668.0    0.07       0  4858.7    0.16       0
  4982.0    0.07       0  4986.9    0.16       0  5060.1   0.035       0
  5154.3    0.07       0  5171.2   0.035       0  5287.5    0.07       0
  5369.7   0.035       0  5389.4    0.07       0
Bank Sta=4982,4986.9
Exp/Cntr=0.3,0.1

Type RM Length L Ch R = 1,3522,305,305,305
BEGIN DESCRIPTION:
Mapping XS 4ca05312
END DESCRIPTION:
XS GIS Cut Line= 3
      1628837.94      6985427.71      1628603.54      6985335.26
      1628205.12      6985188.13
#Sta/Elev= 30
  4746.8 1529.56  4825.2 1527.90  4911.2 1526.83  4925.3 1526.14  4932.7 1526.44
  4979.4 1524.43  4998.8 1522.78  5003.9 1519.16  5009.3 1517.97  5016.1 1517.83
  5016.4 1517.33  5020.6 1517.33  5021.0 1517.83  5029.0 1518.84  5039.9 1519.40
  5050.5 1518.55  5095.2 1519.29  5120.3 1520.41  5150.7 1520.47  5157.1 1521.43
  5181.1 1522.67  5211.6 1523.79  5236.7 1524.09  5292.2 1526.66  5306.4 1526.39
  5315.4 1527.09  5353.0 1528.04  5359.7 1528.84  5413.9 1530.64  5423.5 1530.43
#Mann=4,-1,0
  4746.8   0.035       0  5016.1   0.035       0  5021.0   0.035       0
  5315.4    0.07       0
Bank Sta=5016.1,5021
Exp/Cntr=0.3,0.1

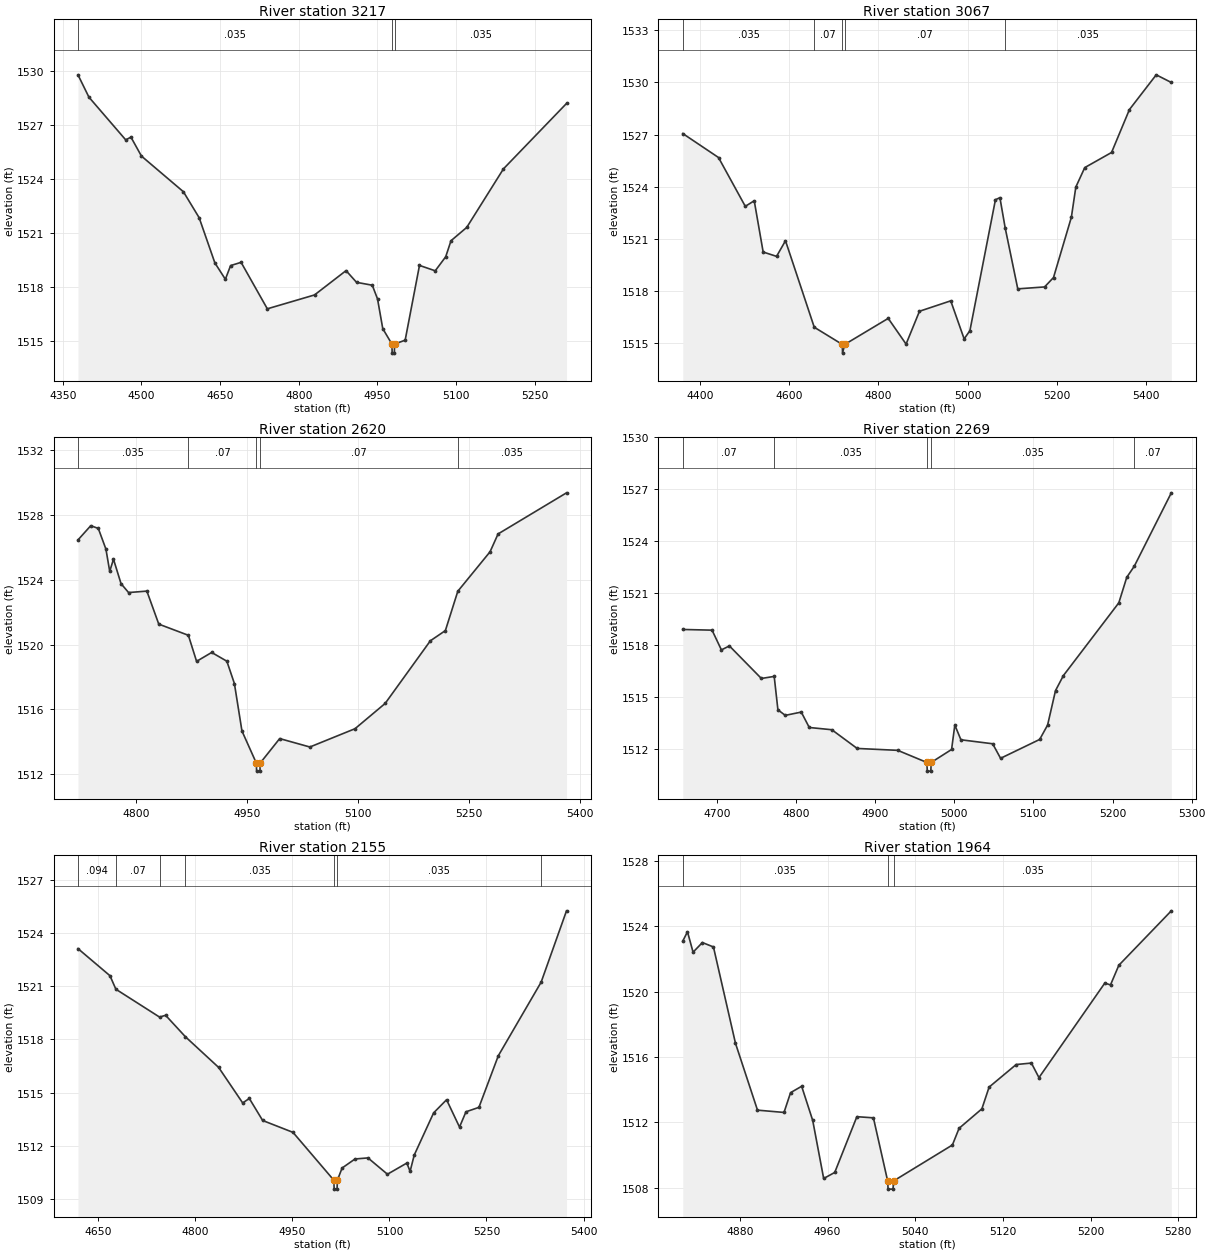
Type RM Length L Ch R = 1,3217,150,150,150
BEGIN DESCRIPTION:
Mapping XS c1e9eefa
END DESCRIPTION:
XS GIS Cut Line= 3
      1629225.94      6985050.10      1628602.24      6985063.12
      1628294.95      6985076.14
#Sta/Elev= 30
  4379.0 1529.78  4399.9 1528.54  4470.0 1526.17  4480.0 1526.32  4500.0 1525.27
  4580.0 1523.29  4610.0 1521.85  4640.0 1519.34  4660.0 1518.43  4670.0 1519.19
  4690.0 1519.37  4740.0 1516.79  4830.0 1517.56  4890.1 1518.91  4910.1 1518.26
  4940.1 1518.10  4950.1 1517.34  4960.1 1515.69  4977.6 1514.83  4978.0 1514.33
  4982.2 1514.33  4982.5 1514.83  5002.8 1515.05  5030.1 1519.20  5060.1 1518.90
  5080.1 1519.68  5090.2 1520.57  5120.2 1521.31  5190.2 1524.56  5310.4 1528.19
#Mann=3,-1,0
  4379.0   0.035       0  4977.6   0.035       0  4982.5   0.035       0
Bank Sta=4977.6,4982.5
Exp/Cntr=0.3,0.1

Type RM Length L Ch R = 1,3067,447,447,447
BEGIN DESCRIPTION:
Mapping XS f9a02da2
END DESCRIPTION:
XS GIS Cut Line= 3
      1629294.94      6984932.91      1628654.33      6984944.63
      1628201.19      6984951.14
#Sta/Elev= 30
  4361.9 1527.06  4441.9 1525.68  4501.9 1522.87  4521.9 1523.19  4541.9 1520.24
  4571.9 1519.99  4591.9 1520.89  4656.3 1515.91  4719.2 1514.92  4719.6 1514.42
  4724.5 1514.92  4821.9 1516.42  4861.9 1514.94  4891.9 1516.83  4961.9 1517.43
  4991.9 1515.24  5004.8 1515.71  5062.0 1523.25  5072.0 1523.37  5083.8 1521.63
  5112.0 1518.12  5172.0 1518.23  5192.0 1518.77  5232.0 1522.24  5242.0 1523.98
  5262.0 1525.10  5322.0 1525.97  5362.0 1528.44  5422.0 1530.44  5455.8 1530.00
#Mann=5,-1,0
  4361.9   0.035       0  4656.3    0.07       0  4719.2    0.07       0
  4724.5    0.07       0  5083.8   0.035       0
Bank Sta=4719.2,4724.5
Exp/Cntr=0.3,0.1

Type RM Length L Ch R = 1,2620,351,351,351
BEGIN DESCRIPTION:
Mapping XS 44193ae0
END DESCRIPTION:
XS GIS Cut Line= 3
      1629291.98      6984831.71      1629019.16      6984775.23
      1628644.13      6984704.75
#Sta/Elev= 30
  4721.4 1526.46  4738.7 1527.34  4748.9 1527.17  4759.2 1525.89  4764.3 1524.52
  4769.4 1525.27  4779.6 1523.76  4789.8 1523.21  4814.5 1523.30  4830.6 1521.26
  4870.6 1520.57  4881.7 1518.96  4902.1 1519.51  4922.6 1518.97  4932.8 1517.59
  4943.0 1514.66  4962.4 1512.68  4962.8 1512.18  4967.3 1512.18  4967.7 1512.68
  4994.0 1514.19  5034.8 1513.67  5095.8 1514.80  5136.5 1516.36  5197.6 1520.23
  5217.9 1520.86  5234.7 1523.29  5278.3 1525.73  5289.1 1526.83  5381.6 1529.37
#Mann=5,-1,0
  4721.4   0.035       0  4870.6    0.07       0  4962.4    0.07       0
  4967.7    0.07       0  5234.7   0.035       0
Bank Sta=4962.4,4967.7
Exp/Cntr=0.3,0.1

Type RM Length L Ch R = 1,2269,114,114,114
BEGIN DESCRIPTION:
Mapping XS 940b91c1
END DESCRIPTION:
XS GIS Cut Line= 4
      1629105.33      6984776.40      1629059.80      6984434.98
      1629054.33      6984338.00      1628878.73      6984334.77
#Sta/Elev= 30
  4657.1 1518.91  4694.1 1518.87  4705.9 1517.73  4716.0 1517.96  4756.4 1516.08
  4772.6 1516.20  4777.3 1514.27  4786.6 1513.95  4806.8 1514.14  4816.9 1513.25
  4845.4 1513.12  4877.4 1512.04  4928.7 1511.93  4965.5 1511.23  4966.0 1510.73
  4970.5 1510.73  4970.9 1511.23  4996.7 1511.98  5000.8 1513.39  5008.5 1512.54
  5048.6 1512.31  5058.6 1511.47  5108.0 1512.56  5118.0 1513.39  5128.0 1515.38
  5138.0 1516.25  5208.0 1520.45  5218.0 1521.92  5227.5 1522.56  5274.3 1526.80
#Mann=5,-1,0
  4657.1    0.07       0  4772.6   0.035       0  4965.5   0.035       0
  4970.9   0.035       0  5227.5    0.07       0
Bank Sta=4965.5,4970.9
Exp/Cntr=0.3,0.1

Type RM Length L Ch R = 1,2155,191,191,191
BEGIN DESCRIPTION:
Mapping XS 3f25a3cf
END DESCRIPTION:
XS GIS Cut Line= 5
      1629264.39      6984713.64      1629173.25      6984497.51
      1629138.51      6984354.74      1629131.37      6984222.98
      1628889.68      6984217.56
#Sta/Elev= 30
  4618.5 1523.12  4668.0 1521.59  4677.1 1520.83  4744.6 1519.26  4754.0 1519.36
  4784.6 1518.15  4836.0 1516.42  4873.1 1514.42  4883.4 1514.67  4904.0 1513.43
  4950.9 1512.76  5014.1 1510.06  5014.5 1509.56  5019.0 1509.56  5019.5 1510.06
  5026.8 1510.75  5046.8 1511.26  5066.8 1511.32  5096.9 1510.40  5126.9 1511.03
  5131.9 1510.56  5138.3 1511.48  5168.3 1513.86  5188.3 1514.60  5208.3 1513.06
  5218.3 1513.92  5238.3 1514.17  5268.3 1517.08  5334.5 1521.23  5373.7 1525.25
#Mann=7,-1,0
  4618.5   0.094       0  4677.1    0.07       0  4744.6   0.094       0
  4784.6   0.035       0  5014.1   0.035       0  5019.5   0.035       0
  5334.5    0.07       0
Bank Sta=5014.1,5019.5
Exp/Cntr=0.3,0.1

Type RM Length L Ch R = 1,1964,143,143,143
BEGIN DESCRIPTION:
Mapping XS 74606f65
END DESCRIPTION:
XS GIS Cut Line= 3
      1629372.76      6984203.69      1629201.97      6984183.56
      1628939.03      6984106.75
#Sta/Elev= 30
  4827.8 1523.09  4832.1 1523.66  4837.2 1522.41  4845.7 1523.00  4855.8 1522.73
  4875.9 1516.84  4896.0 1512.75  4920.2 1512.61  4926.2 1513.82  4936.3 1514.21
  4946.4 1512.12  4956.4 1508.57  4966.5 1508.94  4986.7 1512.35  5001.8 1512.28
  5014.8 1508.42  5015.2 1507.92  5019.7 1507.92  5020.2 1508.42  5073.9 1510.62
  5080.0 1511.64  5100.8 1512.83  5107.4 1514.16  5132.1 1515.54  5146.0 1515.63
  5152.9 1514.74  5213.0 1520.52  5218.2 1520.41  5225.8 1521.61  5273.7 1524.94
#Mann=3,-1,0
  4827.8   0.035       0  5014.8   0.035       0  5020.2   0.035       0
Bank Sta=5014.8,5020.2
Exp/Cntr=0.3,0.1

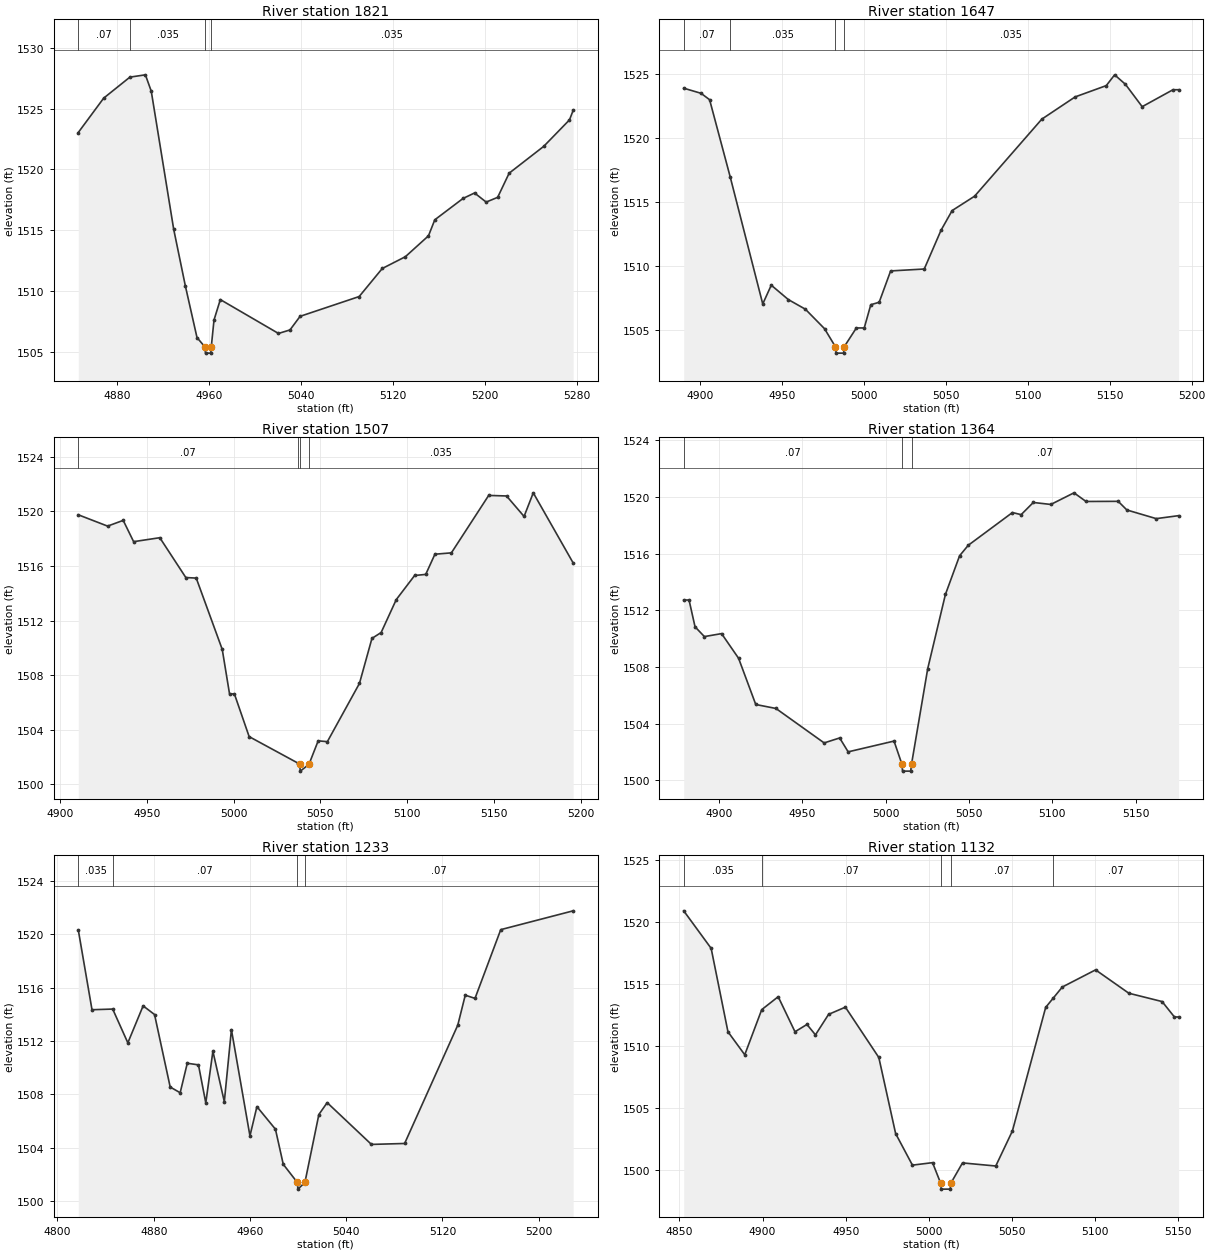
Type RM Length L Ch R = 1,1821,174,174,174
BEGIN DESCRIPTION:
Mapping XS e9273d11
END DESCRIPTION:
XS GIS Cut Line= 3
      1629406.80      6984083.12      1629254.75      6984056.73
      1628979.54      6984032.47
#Sta/Elev= 30
  4846.3 1523.04  4868.4 1525.87  4891.2 1527.60  4904.7 1527.79  4909.8 1526.44
  4929.3 1515.08  4939.5 1510.39  4949.6 1506.15  4956.6 1505.37  4957.0 1504.87
  4961.6 1504.87  4962.0 1505.37  4964.4 1507.60  4969.9 1509.28  5020.5 1506.49
  5030.5 1506.78  5039.3 1507.90  5090.7 1509.53  5110.8 1511.84  5130.9 1512.81
  5151.0 1514.53  5156.5 1515.85  5181.1 1517.61  5191.1 1518.06  5201.2 1517.31
  5211.2 1517.70  5221.2 1519.69  5251.3 1521.90  5273.7 1524.08  5276.9 1524.86
#Mann=4,-1,0
  4846.3    0.07       0  4891.2   0.035       0  4956.6   0.035       0
  4962.0   0.035       0
Bank Sta=4956.6,4962
Exp/Cntr=0.3,0.1

Type RM Length L Ch R = 1,1647,140,140,140
BEGIN DESCRIPTION:
Mapping XS 1ef38fba
END DESCRIPTION:
XS GIS Cut Line= 3
      1629365.84      6983917.49      1629260.82      6983884.51
      1629073.30      6983844.57
#Sta/Elev= 30
  4890.2 1523.86  4900.8 1523.46  4906.0 1522.96  4918.6 1516.93  4938.4 1507.06
  4943.6 1508.52  4954.0 1507.40  4964.4 1506.65  4976.1 1505.13  4982.7 1503.73
  4983.1 1503.23  4987.7 1503.23  4988.1 1503.73  4995.5 1505.19  5000.3 1505.19
  5004.3 1507.00  5009.4 1507.19  5016.4 1509.63  5036.9 1509.78  5047.1 1512.79
  5053.9 1514.33  5067.6 1515.45  5108.6 1521.45  5128.9 1523.18  5147.9 1524.06
  5153.0 1524.90  5159.6 1524.16  5169.8 1522.42  5188.6 1523.74  5192.0 1523.74
#Mann=4,-1,0
  4890.2    0.07       0  4918.6   0.035       0  4982.7   0.035       0
  4988.1   0.035       0
Bank Sta=4982.7,4988.1
Exp/Cntr=0.3,0.1

Type RM Length L Ch R = 1,1507,143,143,143
BEGIN DESCRIPTION:
Mapping XS af45acf8
END DESCRIPTION:
XS GIS Cut Line= 3
      1629427.92      6983829.82      1629353.05      6983779.91
      1629168.75      6983715.24
#Sta/Elev= 30
  4910.4 1519.75  4927.3 1518.92  4936.3 1519.34  4942.3 1517.78  4957.4 1518.07
  4972.4 1515.15  4978.4 1515.11  4993.4 1509.88  4997.6 1506.62  5000.4 1506.62
  5008.9 1503.49  5037.0 1501.55  5038.0 1501.46  5038.4 1500.96  5043.4 1501.46
  5048.7 1503.18  5054.0 1503.12  5072.5 1507.39  5079.7 1510.69  5085.0 1511.12
  5093.7 1513.53  5104.3 1515.30  5110.7 1515.38  5116.0 1516.86  5125.5 1516.96
  5147.0 1521.17  5157.3 1521.13  5167.4 1519.63  5172.7 1521.36  5195.7 1516.22
#Mann=4,-1,0
  4910.4    0.07       0  5037.0   0.035       0  5038.0    0.07       0
  5043.4   0.035       0
Bank Sta=5038,5043.4
Exp/Cntr=0.3,0.1

Type RM Length L Ch R = 1,1364,131,131,131
BEGIN DESCRIPTION:
Mapping XS c7965dcc
END DESCRIPTION:
XS GIS Cut Line= 3
      1629477.14      6983664.39      1629358.48      6983637.77
      1629192.27      6983582.72
#Sta/Elev= 30
  4879.0 1512.72  4882.2 1512.72  4885.8 1510.83  4891.4 1510.14  4901.7 1510.35
  4911.9 1508.61  4922.2 1505.35  4934.3 1505.07  4963.2 1502.64  4972.5 1502.99
  4977.6 1502.01  5005.1 1502.77  5009.8 1501.15  5010.2 1500.65  5015.1 1500.65
  5015.6 1501.15  5025.3 1507.88  5035.9 1513.11  5044.4 1515.84  5049.6 1516.58
  5076.1 1518.89  5081.3 1518.74  5088.6 1519.60  5099.1 1519.46  5113.0 1520.28
  5120.2 1519.67  5139.5 1519.68  5144.7 1519.07  5162.3 1518.46  5175.7 1518.67
#Mann=3,-1,0
  4879.0    0.07       0  5009.8    0.07       0  5015.6    0.07       0
Bank Sta=5009.8,5015.6
Exp/Cntr=0.3,0.1

Type RM Length L Ch R = 1,1233,101,101,101
BEGIN DESCRIPTION:
Mapping XS 2fa36711
END DESCRIPTION:
XS GIS Cut Line= 3
      1629565.75      6983743.05      1629471.33      6983590.02
      1629336.72      6983401.57
#Sta/Elev= 30
  4817.3 1520.33  4828.7 1514.35  4845.9 1514.40  4858.5 1511.87  4871.2 1514.64
  4880.7 1513.99  4893.7 1508.56  4902.0 1508.13  4907.9 1510.34  4917.2 1510.22
  4923.3 1507.37  4929.2 1511.24  4938.7 1507.46  4944.6 1512.86  4960.0 1504.90
  4965.8 1507.09  4981.2 1505.40  4987.7 1502.77  4999.4 1501.41  4999.9 1500.91
  5005.7 1501.41  5017.3 1506.50  5024.2 1507.39  5061.0 1504.26  5088.6 1504.33
  5132.8 1513.20  5139.0 1515.44  5147.1 1515.20  5168.5 1520.35  5228.7 1521.76
#Mann=4,-1,0
  4817.3   0.035       0  4845.9    0.07       0  4999.4    0.07       0
  5005.7    0.07       0
Bank Sta=4999.4,5005.7
Exp/Cntr=0.3,0.1

Type RM Length L Ch R = 1,1132,102,102,102
BEGIN DESCRIPTION:
Mapping XS b2d6211e
END DESCRIPTION:
XS GIS Cut Line= 3
      1629589.61      6983734.38      1629571.15      6983588.94
      1629573.32      6983438.07
#Sta/Elev= 30
  4852.6 1520.89  4869.1 1517.87  4879.2 1511.16  4889.3 1509.31  4899.5 1512.94
  4909.4 1513.98  4919.5 1511.16  4926.7 1511.75  4931.8 1510.91  4939.7 1512.56
  4949.8 1513.14  4969.9 1509.09  4980.0 1502.97  4990.1 1500.43  5002.2 1500.63
  5007.0 1499.00  5007.5 1498.50  5012.8 1498.50  5013.3 1499.00  5020.2 1500.61
  5040.2 1500.36  5050.2 1503.18  5070.2 1513.12  5074.7 1513.86  5080.2 1514.76
  5100.2 1516.14  5120.2 1514.26  5140.2 1513.59  5147.6 1512.35  5150.1 1512.35
#Mann=5,-1,0
  4852.6   0.035       0  4899.5    0.07       0  5007.0    0.07       0
  5013.3    0.07       0  5074.7    0.07       0
Bank Sta=5007,5013.3
Exp/Cntr=0.3,0.1

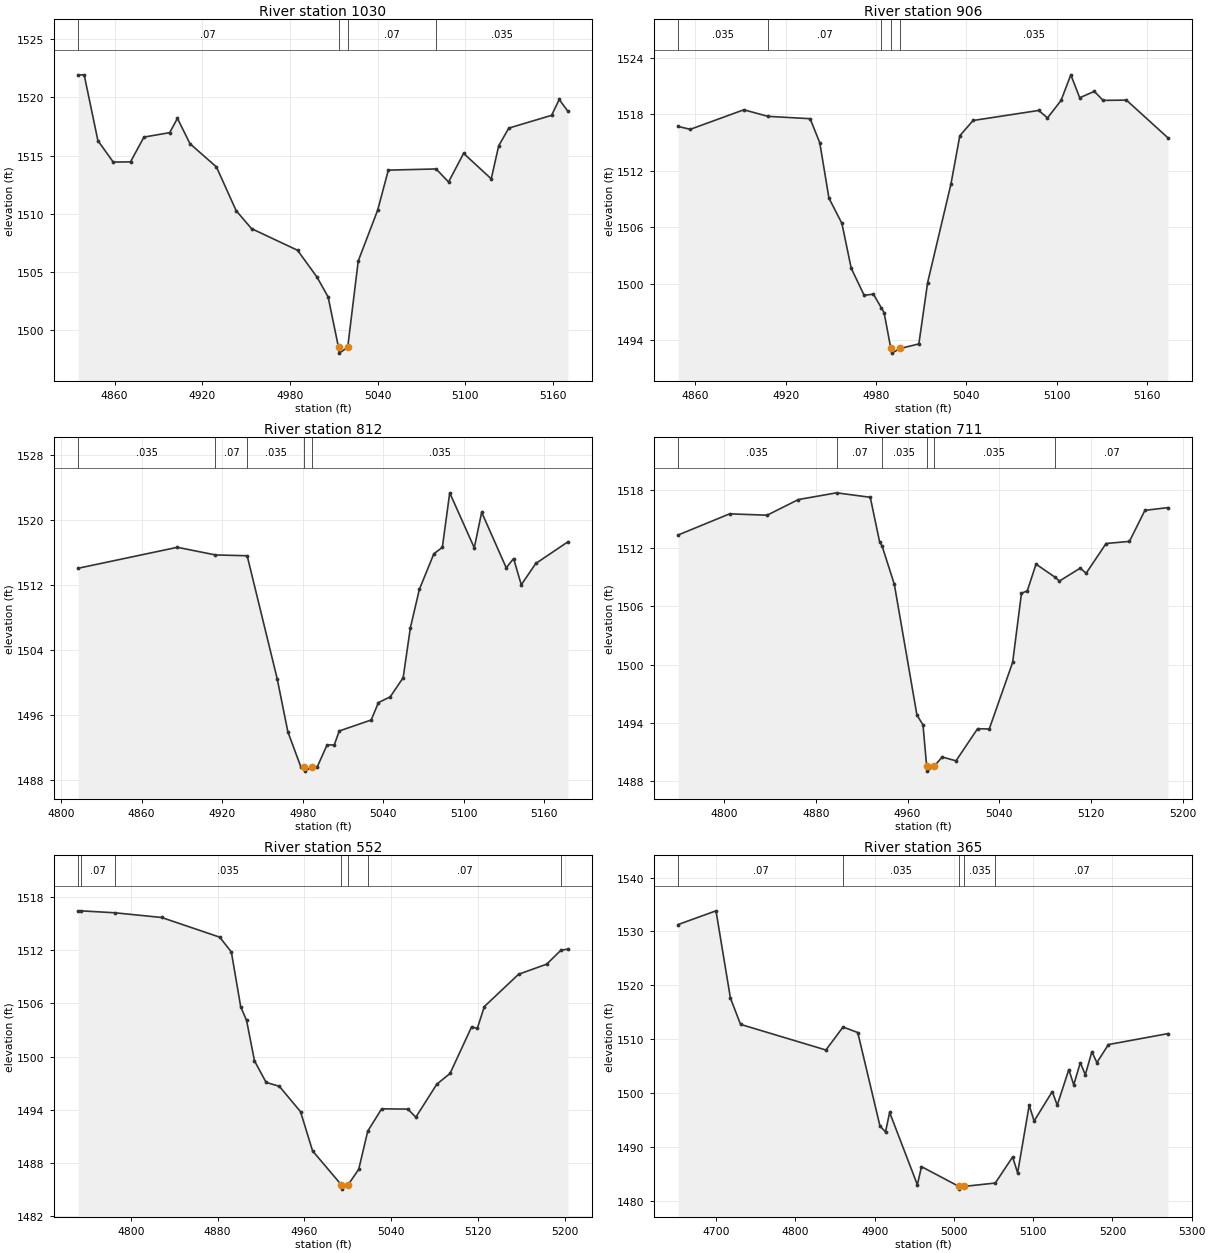
Type RM Length L Ch R = 1,1030,124,124,124
BEGIN DESCRIPTION:
Mapping XS 5234934b
END DESCRIPTION:
XS GIS Cut Line= 3
      1629719.84      6983730.93      1629669.15      6983574.00
      1629628.17      6983408.71
#Sta/Elev= 30
  4835.0 1521.94  4839.2 1521.94  4848.6 1516.28  4859.1 1514.44  4870.9 1514.46
  4880.1 1516.59  4897.7 1516.97  4903.0 1518.20  4911.6 1516.02  4929.7 1514.02
  4943.2 1510.26  4953.7 1508.72  4985.2 1506.86  4998.5 1504.55  5006.1 1502.85
  5013.2 1498.52  5013.7 1498.02  5019.5 1498.52  5026.7 1505.94  5040.0 1510.31
  5047.3 1513.75  5080.0 1513.85  5088.5 1512.73  5098.8 1515.19  5117.7 1513.00
  5122.8 1515.84  5129.7 1517.36  5159.0 1518.46  5164.2 1519.82  5170.2 1518.80
#Mann=4,-1,0
  4835.0    0.07       0  5013.2    0.07       0  5019.5    0.07       0
  5080.0   0.035       0
Bank Sta=5013.2,5019.5
Exp/Cntr=0.3,0.1

Type RM Length L Ch R = 1,906,94,94,94
BEGIN DESCRIPTION:
Mapping XS e20d1f44
END DESCRIPTION:
XS GIS Cut Line= 3
      1629844.81      6983609.37      1629756.65      6983485.80
      1629667.07      6983337.21
#Sta/Elev= 30
  4848.6 1516.72  4856.7 1516.41  4892.3 1518.49  4908.3 1517.79  4936.3 1517.54
  4942.7 1514.99  4948.8 1509.09  4957.4 1506.40  4963.6 1501.62  4972.2 1498.74
  4978.3 1498.87  4983.6 1497.41  4985.4 1496.91  4989.9 1493.09  4990.4 1492.59
  4996.2 1493.09  5008.5 1493.57  5014.3 1500.08  5029.8 1510.58  5035.7 1515.73
  5044.5 1517.35  5088.1 1518.42  5093.9 1517.62  5102.9 1519.48  5109.4 1522.21
  5115.3 1519.77  5125.0 1520.45  5130.8 1519.49  5146.3 1519.52  5173.9 1515.50
#Mann=5,-1,0
  4848.6   0.035       0  4908.3    0.07       0  4983.6   0.035       0
  4989.9   0.035       0  4996.2   0.035       0
Bank Sta=4989.9,4996.2
Exp/Cntr=0.3,0.1

Type RM Length L Ch R = 1,812,101,101,101
BEGIN DESCRIPTION:
Mapping XS 0868f8d3
END DESCRIPTION:
XS GIS Cut Line= 3
      1629900.94      6983590.03      1629822.83      6983419.92
      1629754.26      6983255.86
#Sta/Elev= 30
  4812.6 1514.01  4886.6 1516.59  4915.0 1515.65  4938.6 1515.55  4961.0 1500.40
  4968.9 1493.91  4978.5 1489.62  4980.9 1489.56  4981.4 1489.06  4987.2 1489.56
  4990.9 1489.61  4998.1 1492.28  5003.5 1492.28  5007.2 1494.00  5031.0 1495.35
  5036.4 1497.49  5045.2 1498.20  5054.8 1500.55  5060.2 1506.70  5066.9 1511.42
  5077.7 1515.80  5084.0 1516.58  5089.5 1523.29  5107.8 1516.53  5113.3 1520.90
  5131.6 1514.07  5137.1 1515.21  5142.8 1511.98  5153.6 1514.60  5177.6 1517.27
#Mann=5,-1,0
  4812.6   0.035       0  4915.0    0.07       0  4938.6   0.035       0
  4980.9   0.035       0  4987.2   0.035       0
Bank Sta=4980.9,4987.2
Exp/Cntr=0.3,0.1

Type RM Length L Ch R = 1,711,159,159,159
BEGIN DESCRIPTION:
Mapping XS bc7ee279
END DESCRIPTION:
XS GIS Cut Line= 3
      1629982.56      6983608.31      1629912.24      6983379.99
      1629875.77      6983195.05
#Sta/Elev= 30
  4759.8 1513.33  4804.8 1515.51  4837.5 1515.37  4864.8 1516.98  4898.1 1517.67
  4927.5 1517.21  4935.6 1512.66  4937.9 1512.17  4948.5 1508.26  4968.2 1494.83
  4973.5 1493.81  4976.7 1489.56  4977.2 1489.06  4983.1 1489.56  4990.3 1490.51
  5002.3 1490.12  5021.1 1493.42  5031.3 1493.39  5051.7 1500.24  5059.4 1507.34
  5064.5 1507.60  5072.1 1510.34  5088.5 1509.01  5092.5 1508.60  5110.7 1509.93
  5115.8 1509.40  5133.2 1512.46  5153.6 1512.68  5167.1 1515.87  5187.2 1516.15
#Mann=6,-1,0
  4759.8   0.035       0  4898.1    0.07       0  4937.9   0.035       0
  4976.7   0.035       0  4983.1   0.035       0  5088.5    0.07       0
Bank Sta=4976.7,4983.1
Exp/Cntr=0.3,0.1

Type RM Length L Ch R = 1,552,187,187,187
BEGIN DESCRIPTION:
Mapping XS cc74e22a
END DESCRIPTION:
XS GIS Cut Line= 3
      1630144.01      6983570.09      1630056.33      6983337.45
      1629993.83      6983144.74
#Sta/Elev= 30
  4751.5 1516.44  4754.2 1516.44  4785.3 1516.22  4828.5 1515.69  4882.0 1513.47
  4892.7 1511.80  4901.3 1505.63  4906.7 1504.09  4914.0 1499.53  4924.7 1497.10
  4936.9 1496.66  4956.4 1493.80  4967.5 1489.38  4993.9 1485.57  4994.4 1485.07
  5000.3 1485.57  5010.0 1487.31  5018.3 1491.61  5031.1 1494.12  5055.2 1494.09
  5062.6 1493.18  5081.9 1496.90  5094.1 1498.11  5113.9 1503.35  5119.2 1503.19
  5125.7 1505.65  5157.2 1509.29  5183.1 1510.43  5196.2 1512.00  5202.7 1512.12
#Mann=7,-1,0
  4751.5   0.035       0  4754.2    0.07       0  4785.3   0.035       0
  4993.9   0.035       0  5000.3   0.035       0  5018.3    0.07       0
  5196.2   0.035       0
Bank Sta=4993.9,5000.3
Exp/Cntr=0.3,0.1

Type RM Length L Ch R = 1,365,177,177,177
BEGIN DESCRIPTION:
Mapping XS 99eb6ac0
END DESCRIPTION:
XS GIS Cut Line= 3
      1630317.65      6983724.29      1630228.90      6983390.05
      1630065.47      6983172.15
#Sta/Elev= 30
  4651.9 1531.28  4699.8 1533.83  4718.0 1517.66  4730.8 1512.78  4838.5 1508.03
  4860.1 1512.29  4878.7 1511.27  4906.7 1493.94  4913.7 1492.85  4918.9 1496.46
  4953.9 1483.05  4959.1 1486.41  5006.3 1482.74  5006.8 1482.24  5012.7 1482.74
  5052.2 1483.37  5074.1 1488.20  5080.4 1485.25  5095.0 1497.79  5101.2 1494.87
  5124.1 1500.32  5130.4 1497.80  5145.0 1504.41  5151.2 1501.58  5159.5 1505.68
  5165.8 1503.45  5174.1 1507.71  5180.4 1505.70  5195.0 1509.04  5270.1 1511.07
#Mann=5,-1,0
  4651.9    0.07       0  4860.1   0.035       0  5006.3   0.035       0
  5012.7   0.035       0  5052.2    0.07       0
Bank Sta=5006.3,5012.7
Exp/Cntr=0.3,0.1

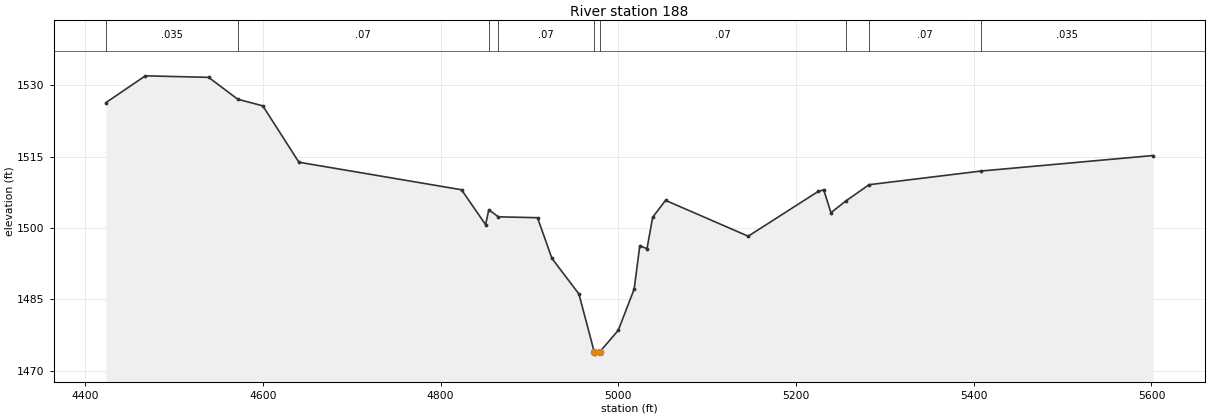
Type RM Length L Ch R = 1,188,0,0,0
BEGIN DESCRIPTION:
Chimney Creek 1131 1.0
END DESCRIPTION:
XS GIS Cut Line= 3
      1630506.89      6983951.73      1630403.54      6983384.47
      1629930.04      6983013.03
#Sta/Elev= 30
  4423.4 1526.39  4467.8 1532.03  4539.0 1531.71  4571.7 1527.12  4600.0 1525.71
  4640.6 1513.86  4823.6 1508.07  4850.7 1500.72  4854.3 1503.87  4865.0 1502.38
  4909.1 1502.19  4925.3 1493.65  4955.7 1486.15  4972.9 1474.00  4973.4 1473.50
  4979.3 1474.00  5000.0 1478.52  5017.9 1487.19  5024.2 1496.30  5032.3 1495.67
  5038.7 1502.29  5053.2 1505.84  5146.2 1498.30  5224.9 1507.71  5231.2 1508.05
  5239.3 1503.25  5256.2 1505.72  5282.2 1509.13  5408.4 1512.01  5601.8 1515.27
#Mann=9,-1,0
  4423.4   0.035       0  4571.7    0.07       0  4854.3   0.035       0
  4865.0    0.07       0  4972.9    0.07       0  4979.3    0.07       0
  5256.2   0.035       0  5282.2    0.07       0  5408.4   0.035       0
Bank Sta=4972.9,4979.3
Exp/Cntr=0.3,0.1

Chan Stop Cuts=-1