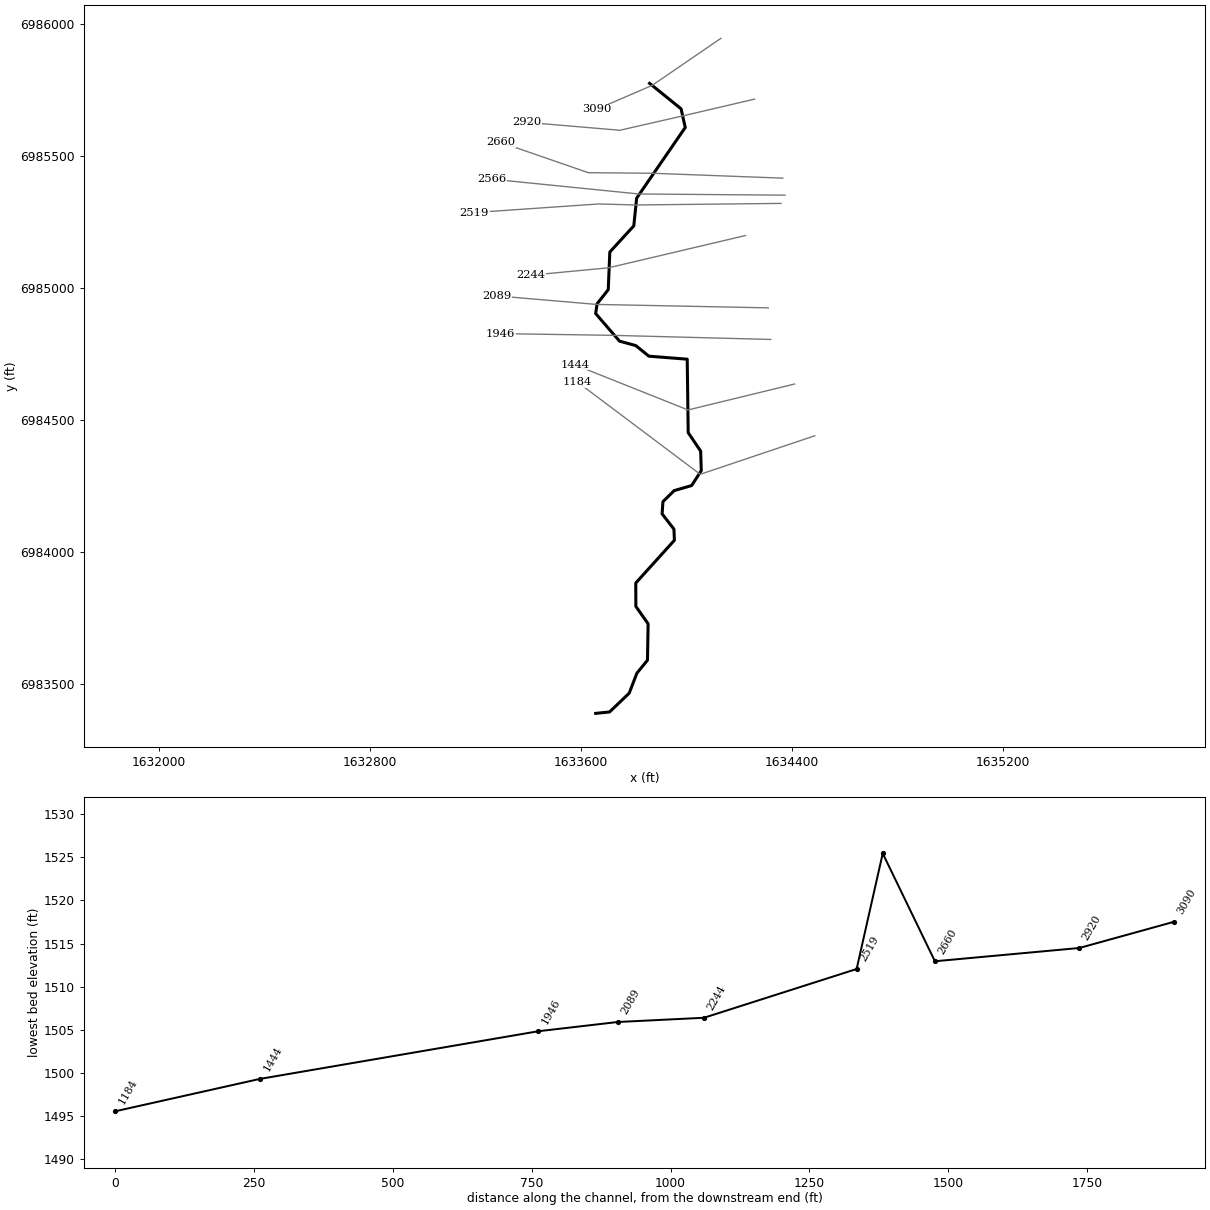
--- Chimney Creek 1132.prj (project) ---

Proj Title=Chimney Creek 1132 Base Level Engineering
Current Plan=p01
Default Exp/Contr=0.3,0.1
English Units
Geom File=g01
Flow File=f01
Plan File=p01
BEGIN DESCRIPTION:
Chimney Creek 1132
END DESCRIPTION:

--- Chimney Creek 1132.p01 (plan) ---

Plan Title=Multiple Run
Short Identifier=Multiple
Geom File=g01
Flow File=f01
Subcritical Flow
K Sum by GR= 0
Std Step Tol= 0.01
Critical Tol= 0.01
Num of Std Step Trials= 20
Max Error Tol= 0.3
Flow Tol Ratio= 0.001
Split Flow NTrial= 30
Split Flow Tol= 0.02
Split Flow Ratio= 0.02
Log Output Level= 0
Friction Slope Method= 1
Unsteady Friction Slope Method= 2
Unsteady Bridges Friction Slope Method= 1
Parabolic Critical Depth
Global Vel Dist=  1 , 1 , 1
Global Log Level= 0
CheckData=True
Encroach Param= -1, 0, 0, 0
BEGIN DESCRIPTION:
Multiple Run
END DESCRIPTION:

--- Chimney Creek 1132.f01 (steady flow) ---

Flow Title=Multiple
Number of Profiles=7
Profile Names=10-year,25-year,50-year,1pct_min,100-year,1pct_plu,500-year
River Rch & RM= Chimney Creek 11,Reach-1,3090
     229     315     385     235     469     935     702
Boundary for River Rch & Prof#=Chimney Creek 11,Reach-1,1
Up Type=0
Dn Type=3
Dn Slope=0.005
Boundary for River Rch & Prof#=Chimney Creek 11,Reach-1,2
Up Type=0
Dn Type=3
Dn Slope=0.005
Boundary for River Rch & Prof#=Chimney Creek 11,Reach-1,3
Up Type=0
Dn Type=3
Dn Slope=0.005
Boundary for River Rch & Prof#=Chimney Creek 11,Reach-1,4
Up Type=0
Dn Type=3
Dn Slope=0.005
Boundary for River Rch & Prof#=Chimney Creek 11,Reach-1,5
Up Type=0
Dn Type=3
Dn Slope=0.005
Boundary for River Rch & Prof#=Chimney Creek 11,Reach-1,6
Up Type=0
Dn Type=3
Dn Slope=0.005
Boundary for River Rch & Prof#=Chimney Creek 11,Reach-1,7
Up Type=0
Dn Type=3
Dn Slope=0.005

--- Chimney Creek 1132.g01 (geometry) ---

Geom Title=Existing Conditions

River Reach=Chimney Creek 11,Reach-1
Reach XY= 30
      1633859.13      6985775.96      1633978.57      6985679.43
      1633994.54      6985608.60      1633810.23      6985340.55
      1633799.48      6985235.57      1633708.56      6985136.53
      1633702.70      6984993.93      1633660.35      6984940.17
      1633654.95      6984903.33      1633745.29      6984798.75
      1633807.17      6984781.86      1633856.56      6984741.76
      1634001.93      6984730.38      1634005.69      6984451.92
      1634052.84      6984382.02      1634055.25      6984307.95
      1634018.63      6984251.46      1633952.41      6984232.24
      1633909.99      6984190.54      1633906.79      6984144.16
      1633951.63      6984086.27      1633953.38      6984044.04
      1633806.96      6983882.11      1633807.28      6983793.57
      1633853.79      6983727.49      1633851.26      6983589.56
      1633811.14      6983540.17      1633782.03      6983464.49
      1633707.54      6983393.30      1633655.00      6983388.00

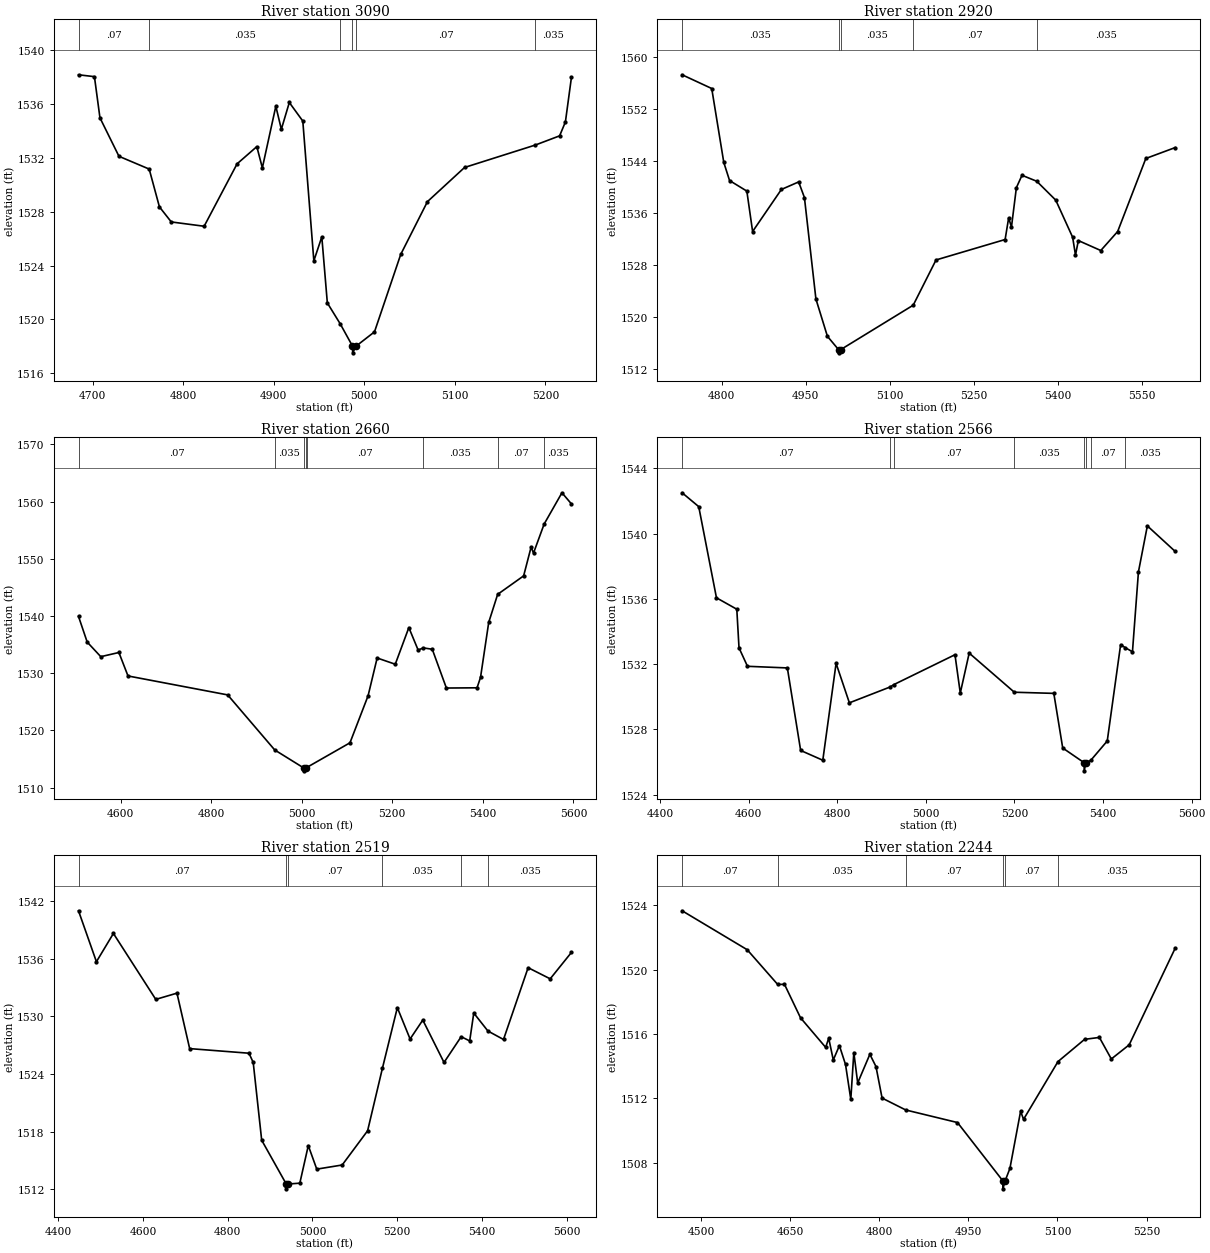
Type RM Length L Ch R = 1,3090,170,170,170
BEGIN DESCRIPTION:
Chimney Creek 1132 5.0
END DESCRIPTION:
XS GIS Cut Line= 3
      1634129.56      6985946.38      1633868.96      6985768.01
      1633658.87      6985677.40
#Sta/Elev= 30
  4684.2 1538.18  4701.8 1538.04  4707.9 1534.98  4728.9 1532.12  4762.3 1531.17
  4773.6 1528.36  4786.7 1527.24  4823.0 1526.92  4859.4 1531.56  4881.2 1532.84
  4887.3 1531.26  4902.2 1535.84  4908.3 1534.13  4917.1 1536.12  4932.0 1534.74
  4944.2 1524.35  4953.0 1526.13  4959.1 1521.22  4973.3 1519.67  4986.9 1518.01
  4987.1 1517.51  4990.9 1518.01  5011.2 1519.07  5040.2 1524.83  5069.7 1528.75
  5110.7 1531.29  5189.0 1532.96  5215.7 1533.64  5222.1 1534.67  5228.8 1538.00
#Mann=6,-1,0
  4684.2    0.07       0  4762.3   0.035       0  4973.3    0.07       0
  4986.9    0.07       0  4990.9    0.07       0  5189.0   0.035       0
Bank Sta=4986.9,4990.9
Exp/Cntr=0.3,0.1

Type RM Length L Ch R = 1,2920,260,260,260
BEGIN DESCRIPTION:
Mapping XS 6bdf45e5
END DESCRIPTION:
XS GIS Cut Line= 4
      1634257.36      6985715.97      1633993.85      6985654.43
      1633746.67      6985597.96      1633392.99      6985628.04
#Sta/Elev= 30
  4729.4 1557.20  4782.2 1555.09  4803.7 1543.73  4814.0 1540.95  4844.8 1539.33
  4855.1 1533.12  4906.4 1539.58  4937.2 1540.74  4947.5 1538.34  4968.0 1522.75
  4988.5 1517.02  5008.3 1514.98  5008.6 1514.48  5012.3 1514.98  5141.5 1521.80
  5182.2 1528.75  5305.4 1531.89  5311.7 1535.21  5316.7 1533.81  5325.5 1539.86
  5335.5 1541.76  5361.8 1540.84  5395.7 1537.94  5425.8 1532.24  5430.9 1529.50
  5436.0 1531.73  5476.0 1530.20  5506.1 1533.12  5556.3 1544.34  5608.5 1546.01
#Mann=5,-1,0
  4729.4   0.035       0  5008.3   0.035       0  5012.3   0.035       0
  5141.5    0.07       0  5361.8   0.035       0
Bank Sta=5008.3,5012.3
Exp/Cntr=0.3,0.1

Type RM Length L Ch R = 1,2660,94,94,94
BEGIN DESCRIPTION:
Mapping XS 8f39b87f
END DESCRIPTION:
XS GIS Cut Line= 4
      1634364.18      6985416.49      1633871.63      6985434.98
      1633627.25      6985437.17      1633295.20      6985551.90
#Sta/Elev= 30
  4507.1 1539.93  4526.3 1535.44  4556.3 1532.89  4596.3 1533.62  4616.4 1529.52
  4836.5 1526.21  4940.4 1516.59  5004.6 1513.44  5004.9 1512.94  5008.6 1513.44
  5011.0 1513.52  5106.6 1517.84  5146.6 1526.06  5166.6 1532.66  5206.6 1531.57
  5236.6 1537.97  5257.1 1534.05  5268.5 1534.42  5288.3 1534.19  5319.5 1527.41
  5387.2 1527.45  5394.9 1529.27  5413.0 1538.89  5432.7 1543.78  5490.1 1547.01
  5506.6 1552.04  5511.9 1550.99  5535.4 1556.07  5574.7 1561.53  5595.7 1559.58
#Mann=8,-1,0
  4507.1    0.07       0  4940.4   0.035       0  5004.6   0.035       0
  5008.6   0.035       0  5011.0    0.07       0  5268.5   0.035       0
  5432.7    0.07       0  5535.4   0.035       0
Bank Sta=5004.6,5008.6
Exp/Cntr=0.3,0.1

Type RM Length L Ch R = 1,2566,47,47,47
BEGIN DESCRIPTION:
Mapping XS 3a295c51
END DESCRIPTION:
XS GIS Cut Line= 3
      1634372.46      6985351.99      1633818.64      6985356.49
      1633262.69      6985412.48
#Sta/Elev= 30
  4450.0 1542.51  4487.5 1541.66  4527.5 1536.07  4573.4 1535.37  4578.4 1533.00
  4597.5 1531.87  4687.5 1531.77  4717.5 1526.71  4767.5 1526.11  4797.5 1532.05
  4827.5 1529.63  4919.3 1530.60  4928.0 1530.75  5065.8 1532.58  5077.8 1530.23
  5097.9 1532.68  5199.8 1530.28  5288.9 1530.21  5309.0 1526.86  5357.3 1525.96
  5357.5 1525.46  5361.3 1525.96  5372.2 1526.10  5409.5 1527.29  5439.7 1533.20
  5450.3 1533.01  5466.4 1532.76  5479.9 1537.66  5500.0 1540.48  5562.6 1538.92
#Mann=8,-1,0
  4450.0    0.07       0  4919.3   0.035       0  4928.0    0.07       0
  5199.8   0.035       0  5357.3    0.07       0  5361.3   0.035       0
  5372.2    0.07       0  5450.3   0.035       0
Bank Sta=5357.3,5361.3
Exp/Cntr=0.3,0.1

Type RM Length L Ch R = 1,2519,275,275,275
BEGIN DESCRIPTION:
Mapping XS 40afea07
END DESCRIPTION:
XS GIS Cut Line= 4
      1634357.35      6985320.74      1633804.31      6985314.83
      1633667.59      6985318.73      1633194.95      6985286.18
#Sta/Elev= 30
  4447.7 1540.97  4490.0 1535.67  4530.1 1538.61  4630.1 1531.75  4680.1 1532.40
  4710.1 1526.63  4850.1 1526.15  4860.1 1525.19  4880.1 1517.10  4938.1 1512.54
  4938.3 1512.04  4942.1 1512.54  4970.1 1512.63  4990.1 1516.54  5010.1 1514.09
  5070.1 1514.52  5130.1 1518.08  5165.1 1524.59  5200.3 1530.89  5230.4 1527.63
  5260.4 1529.60  5310.5 1525.19  5351.0 1527.87  5371.1 1527.43  5380.7 1530.33
  5414.1 1528.46  5450.9 1527.58  5509.0 1535.05  5561.1 1533.89  5611.3 1536.64
#Mann=6,-1,0
  4447.7    0.07       0  4938.1    0.07       0  4942.1    0.07       0
  5165.1   0.035       0  5351.0    0.07       0  5414.1   0.035       0
Bank Sta=4938.1,4942.1
Exp/Cntr=0.3,0.1

Type RM Length L Ch R = 1,2244,155,155,155
BEGIN DESCRIPTION:
Mapping XS 44b45cf2
END DESCRIPTION:
XS GIS Cut Line= 3
      1634222.82      6985199.03      1633704.07      6985076.81
      1633408.07      6985048.52
#Sta/Elev= 30
  4467.8 1523.66  4577.4 1521.24  4628.8 1519.08  4640.2 1519.09  4667.2 1517.01
  4709.6 1515.17  4714.7 1515.74  4722.4 1514.39  4732.7 1515.28  4743.0 1514.11
  4751.9 1511.94  4757.0 1514.85  4763.5 1512.96  4784.0 1514.74  4794.3 1513.98
  4804.6 1512.02  4844.5 1511.28  4931.6 1510.50  5007.9 1506.88  5008.1 1506.38
  5011.9 1506.88  5019.9 1507.65  5037.9 1511.20  5042.9 1510.70  5100.9 1514.29
  5145.7 1515.67  5170.6 1515.79  5190.7 1514.45  5220.8 1515.33  5298.1 1521.32
#Mann=6,-1,0
  4467.8    0.07       0  4628.8   0.035       0  4844.5    0.07       0
  5007.9    0.07       0  5011.9    0.07       0  5100.9   0.035       0
Bank Sta=5007.9,5011.9
Exp/Cntr=0.3,0.1

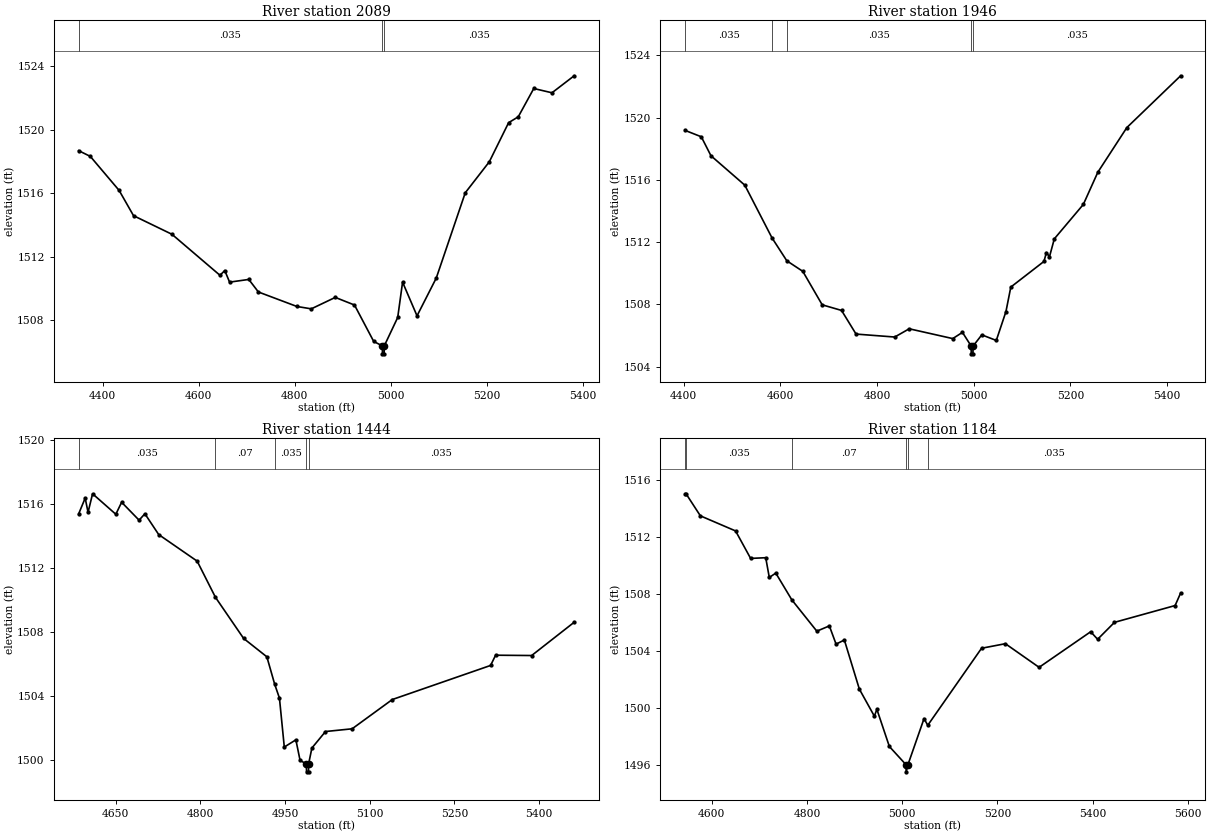
Type RM Length L Ch R = 1,2089,143,143,143
BEGIN DESCRIPTION:
Mapping XS 24f7753e
END DESCRIPTION:
XS GIS Cut Line= 3
      1634309.27      6984924.92      1633658.27      6984937.94
      1633278.99      6984970.42
#Sta/Elev= 30
  4349.8 1518.67  4374.1 1518.31  4434.1 1516.17  4464.1 1514.58  4544.1 1513.41
  4644.1 1510.83  4654.1 1511.13  4664.1 1510.40  4704.1 1510.57  4724.1 1509.78
  4804.2 1508.87  4834.2 1508.72  4884.2 1509.44  4924.2 1508.96  4964.2 1506.67
  4982.2 1506.39  4982.4 1505.89  4985.9 1505.89  4986.2 1506.39  5014.2 1508.18
  5024.3 1510.40  5054.4 1508.28  5094.5 1510.66  5154.8 1516.02  5204.9 1517.97
  5245.1 1520.43  5265.2 1520.80  5297.5 1522.58  5335.4 1522.31  5381.6 1523.38
#Mann=3,-1,0
  4349.8   0.035       0  4982.2   0.035       0  4986.2   0.035       0
Bank Sta=4982.2,4986.2
Exp/Cntr=0.3,0.1

Type RM Length L Ch R = 1,1946,502,502,502
BEGIN DESCRIPTION:
Mapping XS 751728b3
END DESCRIPTION:
XS GIS Cut Line= 3
      1634318.46      6984805.13      1633719.47      6984820.76
      1633293.71      6984827.27
#Sta/Elev= 30
  4403.0 1519.18  4436.5 1518.77  4456.5 1517.55  4526.5 1515.66  4582.8 1512.27
  4613.4 1510.80  4646.5 1510.12  4686.6 1507.97  4726.6 1507.61  4756.6 1506.09
  4836.6 1505.90  4866.6 1506.43  4956.6 1505.80  4976.7 1506.20  4994.7 1505.32
  4994.9 1504.82  4998.4 1504.82  4998.7 1505.32  5016.7 1506.04  5046.7 1505.68
  5066.7 1507.54  5076.7 1509.11  5145.3 1510.76  5150.3 1511.33  5156.7 1511.06
  5166.7 1512.21  5226.7 1514.42  5256.7 1516.49  5316.7 1519.36  5428.0 1522.69
#Mann=5,-1,0
  4403.0   0.035       0  4582.8    0.07       0  4613.4   0.035       0
  4994.7   0.035       0  4998.7   0.035       0
Bank Sta=4994.7,4998.7
Exp/Cntr=0.3,0.1

Type RM Length L Ch R = 1,1444,260,260,260
BEGIN DESCRIPTION:
Mapping XS ea7c15a9
END DESCRIPTION:
XS GIS Cut Line= 3
      1634409.04      6984636.27      1634004.93      6984537.97
      1633575.72      6984709.19
#Sta/Elev= 30
  4584.1 1515.40  4595.7 1516.39  4600.8 1515.50  4608.8 1516.66  4650.0 1515.38
  4660.3 1516.13  4691.2 1515.01  4701.5 1515.41  4726.0 1514.11  4794.1 1512.45
  4826.5 1510.19  4876.4 1507.62  4917.6 1506.47  4931.6 1504.74  4939.9 1503.89
  4948.5 1500.83  4969.0 1501.28  4976.5 1499.99  4987.6 1499.78  4987.9 1499.28
  4991.4 1499.28  4991.6 1499.78  4997.4 1500.77  5021.5 1501.80  5068.7 1501.97
  5139.9 1503.80  5314.0 1505.93  5322.9 1506.57  5386.8 1506.55  5462.1 1508.63
#Mann=5,-1,0
  4584.1   0.035       0  4826.5    0.07       0  4931.6   0.035       0
  4987.6   0.035       0  4991.6   0.035       0
Bank Sta=4987.6,4991.6
Exp/Cntr=0.3,0.1

Type RM Length L Ch R = 1,1184,0,0,0
BEGIN DESCRIPTION:
Mapping XS 7b20ce2e
END DESCRIPTION:
XS GIS Cut Line= 3
      1634485.45      6984440.10      1634051.28      6984294.06
      1633585.69      6984643.98
#Sta/Elev= 30
  4544.1 1515.06  4546.1 1515.06  4576.2 1513.51  4650.1 1512.45  4681.7 1510.52
  4713.4 1510.57  4720.9 1509.18  4734.5 1509.49  4768.2 1507.61  4820.7 1505.41
  4847.0 1505.78  4861.1 1504.50  4878.5 1504.79  4910.0 1501.34  4941.5 1499.44
  4946.8 1499.92  4973.0 1497.31  5008.0 1496.03  5008.3 1495.53  5012.0 1496.03
  5045.8 1499.27  5053.6 1498.80  5166.6 1504.21  5216.6 1504.53  5287.4 1502.87
  5395.7 1505.37  5410.3 1504.84  5445.7 1506.03  5573.0 1507.21  5584.6 1508.09
#Mann=6,-1,0
  4544.1    0.07       0  4546.1   0.035       0  4768.2    0.07       0
  5008.0    0.07       0  5012.0    0.07       0  5053.6   0.035       0
Bank Sta=5008,5012
Exp/Cntr=0.3,0.1

Chan Stop Cuts=-1