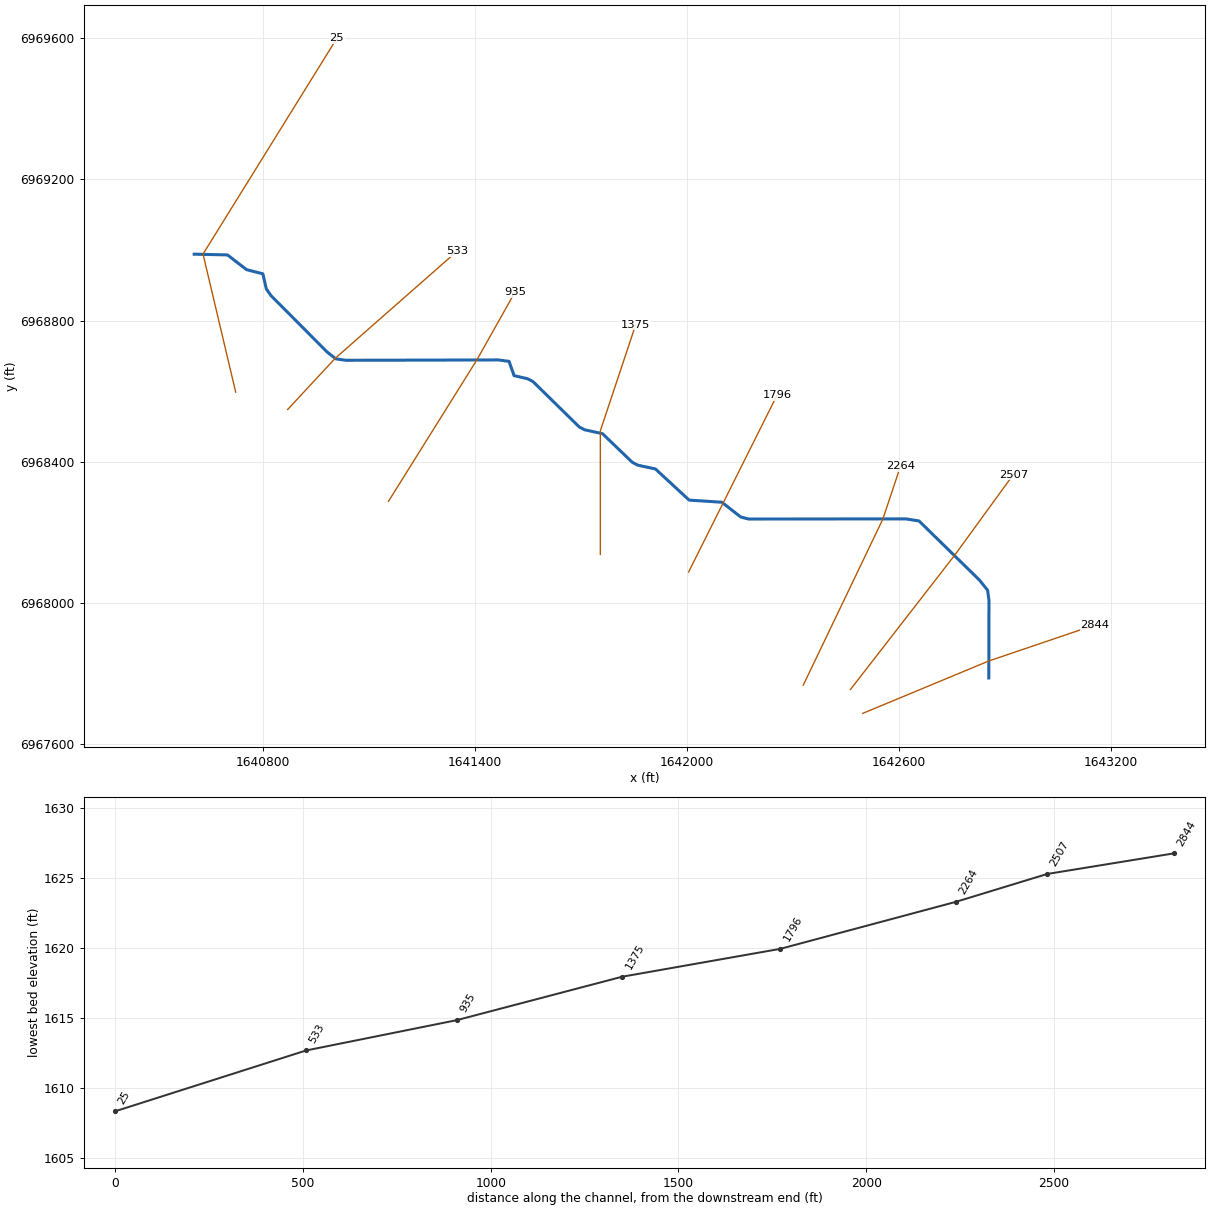
--- Chimney Creek 1134.prj (project) ---

Proj Title=Chimney Creek 1134 Base Level Engineering
Current Plan=p01
Default Exp/Contr=0.3,0.1
English Units
Geom File=g01
Flow File=f01
Plan File=p01
BEGIN DESCRIPTION:
Chimney Creek 1134
END DESCRIPTION:

--- Chimney Creek 1134.p01 (plan) ---

Plan Title=Multiple Run
Short Identifier=Multiple
Geom File=g01
Flow File=f01
Subcritical Flow
K Sum by GR= 0
Std Step Tol= 0.01
Critical Tol= 0.01
Num of Std Step Trials= 20
Max Error Tol= 0.3
Flow Tol Ratio= 0.001
Split Flow NTrial= 30
Split Flow Tol= 0.02
Split Flow Ratio= 0.02
Log Output Level= 0
Friction Slope Method= 1
Unsteady Friction Slope Method= 2
Unsteady Bridges Friction Slope Method= 1
Parabolic Critical Depth
Global Vel Dist=  1 , 1 , 1
Global Log Level= 0
CheckData=True
Encroach Param= -1, 0, 0, 0
BEGIN DESCRIPTION:
Multiple Run
END DESCRIPTION:

--- Chimney Creek 1134.f01 (steady flow) ---

Flow Title=Multiple
Number of Profiles=7
Profile Names=10-year,25-year,50-year,1pct_min,100-year,1pct_plu,500-year
River Rch & RM= Chimney Creek 11,Reach-1,2844
     210     286     348     211     420     838     621
River Rch & RM= Chimney Creek 11,Reach-1,1375
     217     296     360     218     436     869     645
River Rch & RM= Chimney Creek 11,Reach-1,25
     499     708     886     550    1097    2189    1707
Boundary for River Rch & Prof#=Chimney Creek 11,Reach-1,1
Up Type=0
Dn Type=3
Dn Slope=0.005
Boundary for River Rch & Prof#=Chimney Creek 11,Reach-1,2
Up Type=0
Dn Type=3
Dn Slope=0.005
Boundary for River Rch & Prof#=Chimney Creek 11,Reach-1,3
Up Type=0
Dn Type=3
Dn Slope=0.005
Boundary for River Rch & Prof#=Chimney Creek 11,Reach-1,4
Up Type=0
Dn Type=3
Dn Slope=0.005
Boundary for River Rch & Prof#=Chimney Creek 11,Reach-1,5
Up Type=0
Dn Type=3
Dn Slope=0.005
Boundary for River Rch & Prof#=Chimney Creek 11,Reach-1,6
Up Type=0
Dn Type=3
Dn Slope=0.005
Boundary for River Rch & Prof#=Chimney Creek 11,Reach-1,7
Up Type=0
Dn Type=3
Dn Slope=0.005

--- Chimney Creek 1134.g01 (geometry) ---

Geom Title=Existing Conditions

River Reach=Chimney Creek 11,Reach-1
Reach XY= 30
      1642855.00      6967788.00      1642855.43      6968008.18
      1642851.47      6968036.54      1642828.83      6968064.87
      1642657.45      6968232.54      1642620.20      6968238.49
      1642175.03      6968238.07      1642152.66      6968243.74
      1642099.02      6968285.64      1642006.50      6968291.62
      1641911.04      6968379.82      1641861.05      6968390.54
      1641845.33      6968398.80      1641761.04      6968479.82
      1641711.05      6968490.53      1641695.32      6968498.78
      1641564.43      6968627.15      1641549.02      6968635.29
      1641510.80      6968644.06      1641496.56      6968684.60
      1641465.54      6968688.55      1641034.82      6968687.57
      1641006.46      6968691.54      1640981.47      6968710.86
      1640821.73      6968871.52      1640809.13      6968890.01
      1640799.39      6968932.41      1640753.16      6968944.25
      1640699.17      6968985.94      1640605.00      6968988.00

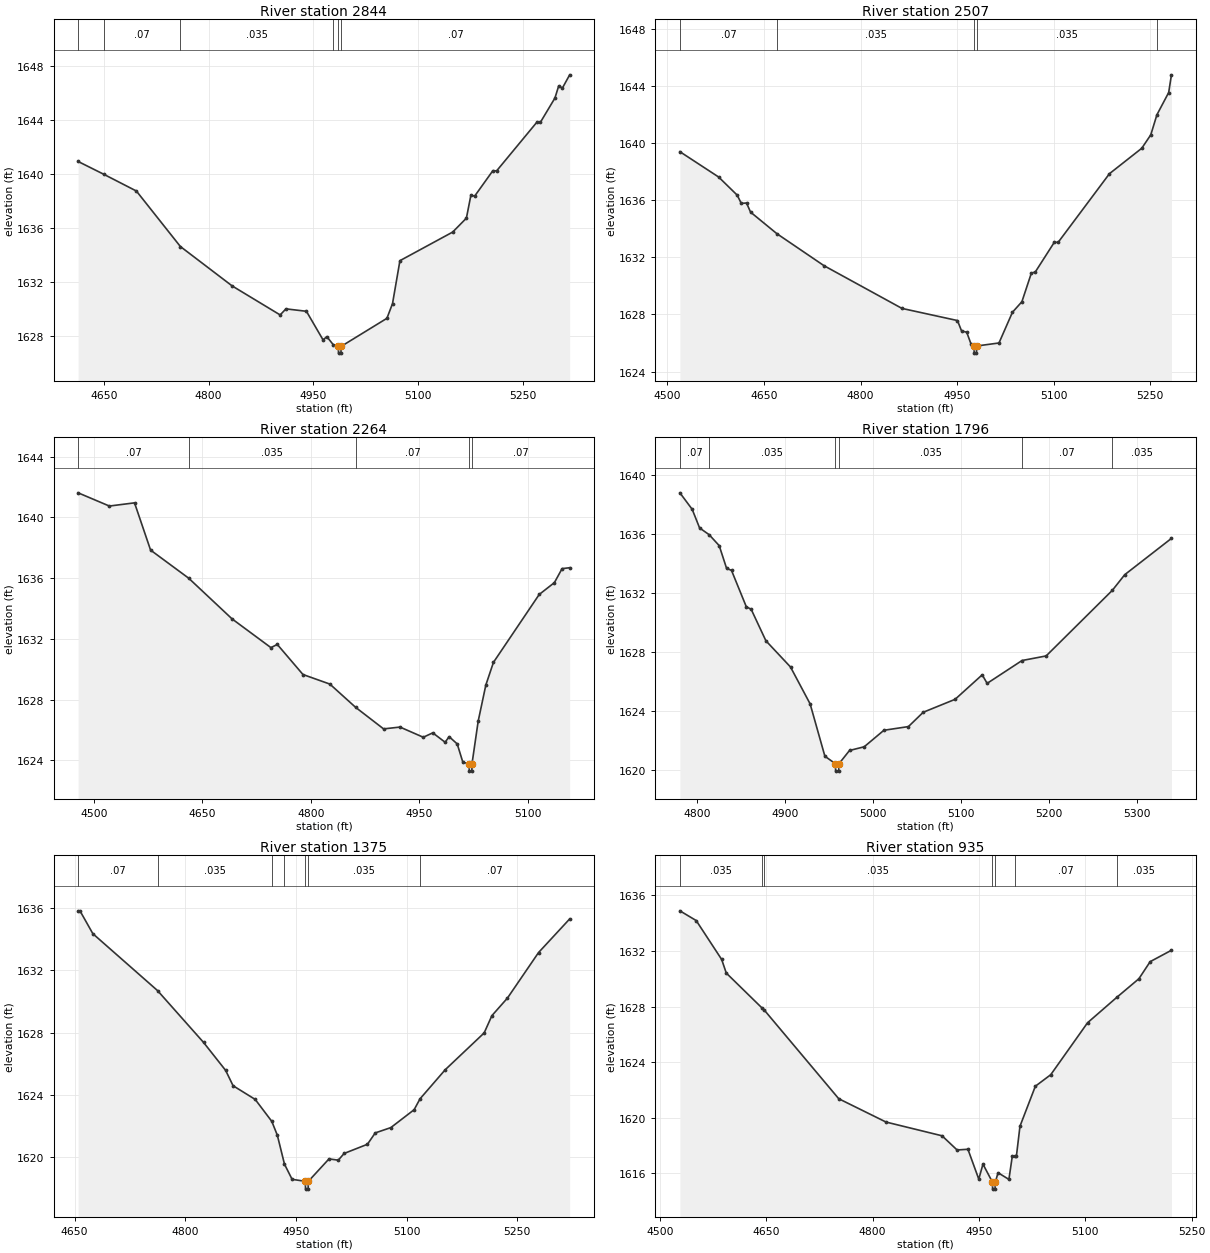
Type RM Length L Ch R = 1,2844,337,337,337
BEGIN DESCRIPTION:
Chimney Creek 1134 6.0
END DESCRIPTION:
XS GIS Cut Line= 3
      1642498.02      6967687.78      1642855.02      6967836.14
      1643154.99      6967938.00
#Sta/Elev= 30
  4613.4 1640.96  4649.8 1640.02  4696.8 1638.77  4759.7 1634.66  4833.8 1631.74
  4902.5 1629.59  4910.8 1630.04  4940.1 1629.86  4963.9 1627.74  4969.3 1627.98
  4978.4 1627.39  4985.8 1627.26  4986.0 1626.76  4989.5 1626.76  4989.8 1627.26
  5055.3 1629.34  5063.3 1630.43  5073.9 1633.61  5149.4 1635.73  5169.0 1636.76
  5175.5 1638.47  5180.8 1638.39  5206.9 1640.28  5212.2 1640.26  5269.7 1643.86
  5275.0 1643.87  5295.7 1645.66  5301.1 1646.56  5306.4 1646.40  5316.8 1647.38
#Mann=6,-1,0
  4613.4   0.035       0  4649.8    0.07       0  4759.7   0.035       0
  4978.4    0.07       0  4985.8    0.07       0  4989.8    0.07       0
Bank Sta=4985.8,4989.8
Exp/Cntr=0.3,0.1

Type RM Length L Ch R = 1,2507,243,243,243
BEGIN DESCRIPTION:
Mapping XS 196e88fc
END DESCRIPTION:
XS GIS Cut Line= 3
      1642463.25      6967755.46      1642758.40      6968135.68
      1642924.42      6968363.96
#Sta/Elev= 30
  4519.4 1639.39  4579.5 1637.62  4608.4 1636.35  4614.8 1635.77  4622.9 1635.80
  4629.2 1635.16  4670.1 1633.65  4743.3 1631.41  4864.4 1628.42  4950.6 1627.57
  4956.9 1626.85  4965.0 1626.75  4971.4 1625.96  4976.4 1625.79  4976.6 1625.29
  4980.1 1625.29  4980.4 1625.79  5015.1 1626.00  5036.0 1628.15  5050.7 1628.89
  5065.4 1630.89  5071.5 1630.97  5100.9 1633.04  5107.1 1633.05  5186.7 1637.85
  5236.9 1639.63  5250.9 1640.57  5260.4 1641.97  5278.7 1643.53  5283.0 1644.77
#Mann=5,-1,0
  4519.4    0.07       0  4670.1   0.035       0  4976.4   0.035       0
  4980.4   0.035       0  5260.4    0.07       0
Bank Sta=4976.4,4980.4
Exp/Cntr=0.3,0.1

Type RM Length L Ch R = 1,2264,468,468,468
BEGIN DESCRIPTION:
Chimney Creek 1134 5.0
END DESCRIPTION:
XS GIS Cut Line= 3
      1642329.58      6967767.62      1642555.00      6968238.00
      1642604.99      6968387.98
#Sta/Elev= 30
  4478.3 1641.62  4521.5 1640.75  4556.3 1640.96  4578.5 1637.85  4631.2 1636.00
  4691.2 1633.32  4744.9 1631.43  4753.7 1631.64  4789.2 1629.66  4826.4 1629.03
  4862.0 1627.50  4900.7 1626.08  4923.4 1626.20  4955.6 1625.53  4968.7 1625.82
  4985.8 1625.20  4991.3 1625.57  5002.5 1625.09  5010.4 1623.87  5019.0 1623.80
  5019.2 1623.30  5022.7 1623.30  5023.0 1623.80  5031.5 1626.59  5042.1 1628.97
  5052.6 1630.46  5115.9 1634.93  5136.9 1635.71  5147.5 1636.63  5158.0 1636.69
#Mann=5,-1,0
  4478.3    0.07       0  4631.2   0.035       0  4862.0    0.07       0
  5019.0    0.07       0  5023.0    0.07       0
Bank Sta=5019,5023
Exp/Cntr=0.3,0.1

Type RM Length L Ch R = 1,1796,421,421,421
BEGIN DESCRIPTION:
Chimney Creek 1134 4.0
END DESCRIPTION:
XS GIS Cut Line= 3
      1642005.00      6968088.00      1642105.00      6968288.00
      1642254.99      6968587.98
#Sta/Elev= 30
  4780.6 1638.81  4794.6 1637.69  4803.0 1636.43  4813.9 1635.97  4825.3 1635.23
  4833.7 1633.69  4839.3 1633.55  4856.1 1631.09  4861.7 1630.91  4878.4 1628.78
  4906.4 1627.00  4928.7 1624.50  4945.5 1620.95  4957.5 1620.44  4957.7 1619.94
  4961.2 1619.94  4961.5 1620.44  4973.5 1621.34  4990.2 1621.59  5012.6 1622.71
  5040.5 1622.96  5057.3 1623.93  5093.6 1624.81  5124.4 1626.47  5130.0 1625.89
  5169.7 1627.44  5197.1 1627.75  5272.4 1632.20  5286.5 1633.26  5339.6 1635.72
#Mann=6,-1,0
  4780.6    0.07       0  4813.9   0.035       0  4957.5   0.035       0
  4961.5   0.035       0  5169.7    0.07       0  5272.4   0.035       0
Bank Sta=4957.5,4961.5
Exp/Cntr=0.3,0.1

Type RM Length L Ch R = 1,1375,440,440,440
BEGIN DESCRIPTION:
Chimney Creek 1134 3.0
END DESCRIPTION:
XS GIS Cut Line= 3
      1641755.00      6968138.02      1641755.00      6968488.00
      1641855.00      6968788.00
#Sta/Elev= 30
  4654.8 1635.82  4657.3 1635.82  4674.8 1634.35  4762.4 1630.70  4824.8 1627.37
  4854.8 1625.57  4864.8 1624.59  4894.8 1623.71  4917.3 1622.30  4924.8 1621.41
  4934.5 1619.55  4944.8 1618.58  4962.8 1618.45  4963.0 1617.95  4966.5 1617.95
  4966.8 1618.45  4994.8 1619.89  5007.4 1619.81  5015.3 1620.24  5046.9 1620.83
  5057.5 1621.56  5078.6 1621.90  5110.2 1623.05  5118.2 1623.75  5152.4 1625.62
  5205.1 1627.98  5215.6 1629.09  5236.7 1630.22  5278.8 1633.14  5321.0 1635.30
#Mann=7,-1,0
  4654.8    0.07       0  4762.4   0.035       0  4917.3    0.07       0
  4934.5   0.035       0  4962.8   0.035       0  4966.8   0.035       0
  5118.2    0.07       0
Bank Sta=4962.8,4966.8
Exp/Cntr=0.3,0.1

Type RM Length L Ch R = 1,935,402,402,402
BEGIN DESCRIPTION:
Chimney Creek 1134 2.0
END DESCRIPTION:
XS GIS Cut Line= 3
      1641155.02      6968288.03      1641405.00      6968688.00
      1641513.63      6968881.07
#Sta/Elev= 30
  4528.2 1634.89  4551.2 1634.19  4587.1 1631.39  4593.6 1630.41  4643.5 1627.92
  4646.6 1627.78  4752.2 1621.36  4818.9 1619.68  4897.9 1618.69  4919.1 1617.67
  4934.4 1617.72  4949.7 1615.57  4955.6 1616.65  4969.0 1615.35  4969.2 1614.85
  4972.7 1614.85  4973.0 1615.35  4976.9 1616.03  4992.2 1615.55  4996.9 1617.20
  5001.1 1617.20  5002.7 1617.20  5007.8 1619.38  5029.5 1622.26  5051.2 1623.09
  5103.1 1626.83  5144.1 1628.65  5175.5 1630.00  5191.4 1631.23  5221.4 1632.05
#Mann=7,-1,0
  4528.2   0.035       0  4643.5    0.07       0  4646.6   0.035       0
  4969.0   0.035       0  4973.0   0.035       0  5001.1    0.07       0
  5144.1   0.035       0
Bank Sta=4969,4973
Exp/Cntr=0.3,0.1

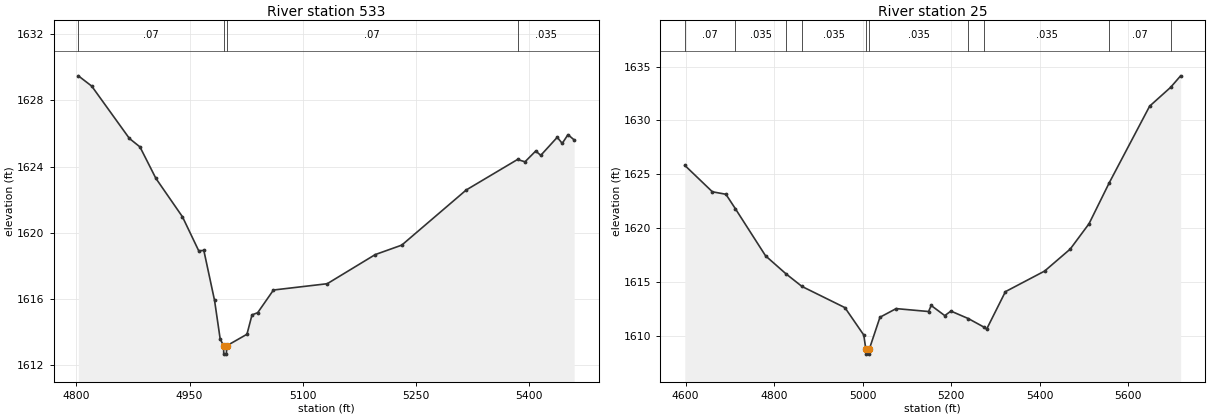
Type RM Length L Ch R = 1,533,508,508,508
BEGIN DESCRIPTION:
Mapping XS 076ee4dd
END DESCRIPTION:
XS GIS Cut Line= 3
      1640869.68      6968548.18      1641003.80      6968692.71
      1641348.83      6968996.08
#Sta/Elev= 30
  4802.7 1629.48  4820.4 1628.86  4870.3 1625.70  4884.3 1625.19  4905.4 1623.29
  4940.6 1620.97  4962.1 1618.92  4968.9 1618.94  4983.1 1615.92  4990.5 1613.61
  4995.0 1613.18  4995.3 1612.68  4998.8 1612.68  4999.1 1613.18  5026.0 1613.88
  5032.7 1615.05  5040.2 1615.18  5061.1 1616.55  5132.3 1616.93  5195.9 1618.69
  5231.0 1619.26  5316.4 1622.59  5384.3 1624.43  5394.2 1624.29  5408.4 1624.94
  5415.1 1624.68  5436.9 1625.77  5443.5 1625.40  5451.1 1625.93  5459.3 1625.61
#Mann=4,-1,0
  4802.7    0.07       0  4995.0    0.07       0  4999.1    0.07       0
  5384.3   0.035       0
Bank Sta=4995,4999.1
Exp/Cntr=0.3,0.1

Type RM Length L Ch R = 1,25,0,0,0
BEGIN DESCRIPTION:
Chimney Creek 1134 1.0
END DESCRIPTION:
XS GIS Cut Line= 3
      1640722.53      6968597.39      1640630.00      6968988.28
      1641008.98      6969599.17
#Sta/Elev= 30
  4598.3 1625.84  4660.6 1623.39  4691.2 1623.16  4712.3 1621.84  4780.9 1617.45
  4827.4 1615.77  4863.3 1614.61  4960.2 1612.65  5002.8 1610.11  5007.3 1608.84
  5007.8 1608.34  5015.1 1608.34  5015.6 1608.84  5039.4 1611.76  5076.0 1612.56
  5149.3 1612.29  5155.1 1612.85  5185.9 1611.91  5199.7 1612.33  5239.4 1611.63
  5275.5 1610.82  5280.4 1610.65  5322.9 1614.13  5411.5 1616.04  5469.4 1618.08
  5511.9 1620.43  5557.4 1624.21  5648.9 1631.33  5696.2 1633.07  5718.9 1634.14
#Mann=10,-1,0
  4598.3    0.07       0  4712.3   0.035       0  4827.4    0.07       0
  4863.3   0.035       0  5007.3   0.035       0  5015.6   0.035       0
  5239.4    0.07       0  5275.5   0.035       0  5557.4    0.07       0
  5696.2   0.035       0
Bank Sta=5007.3,5015.6
Exp/Cntr=0.3,0.1

Chan Stop Cuts=-1