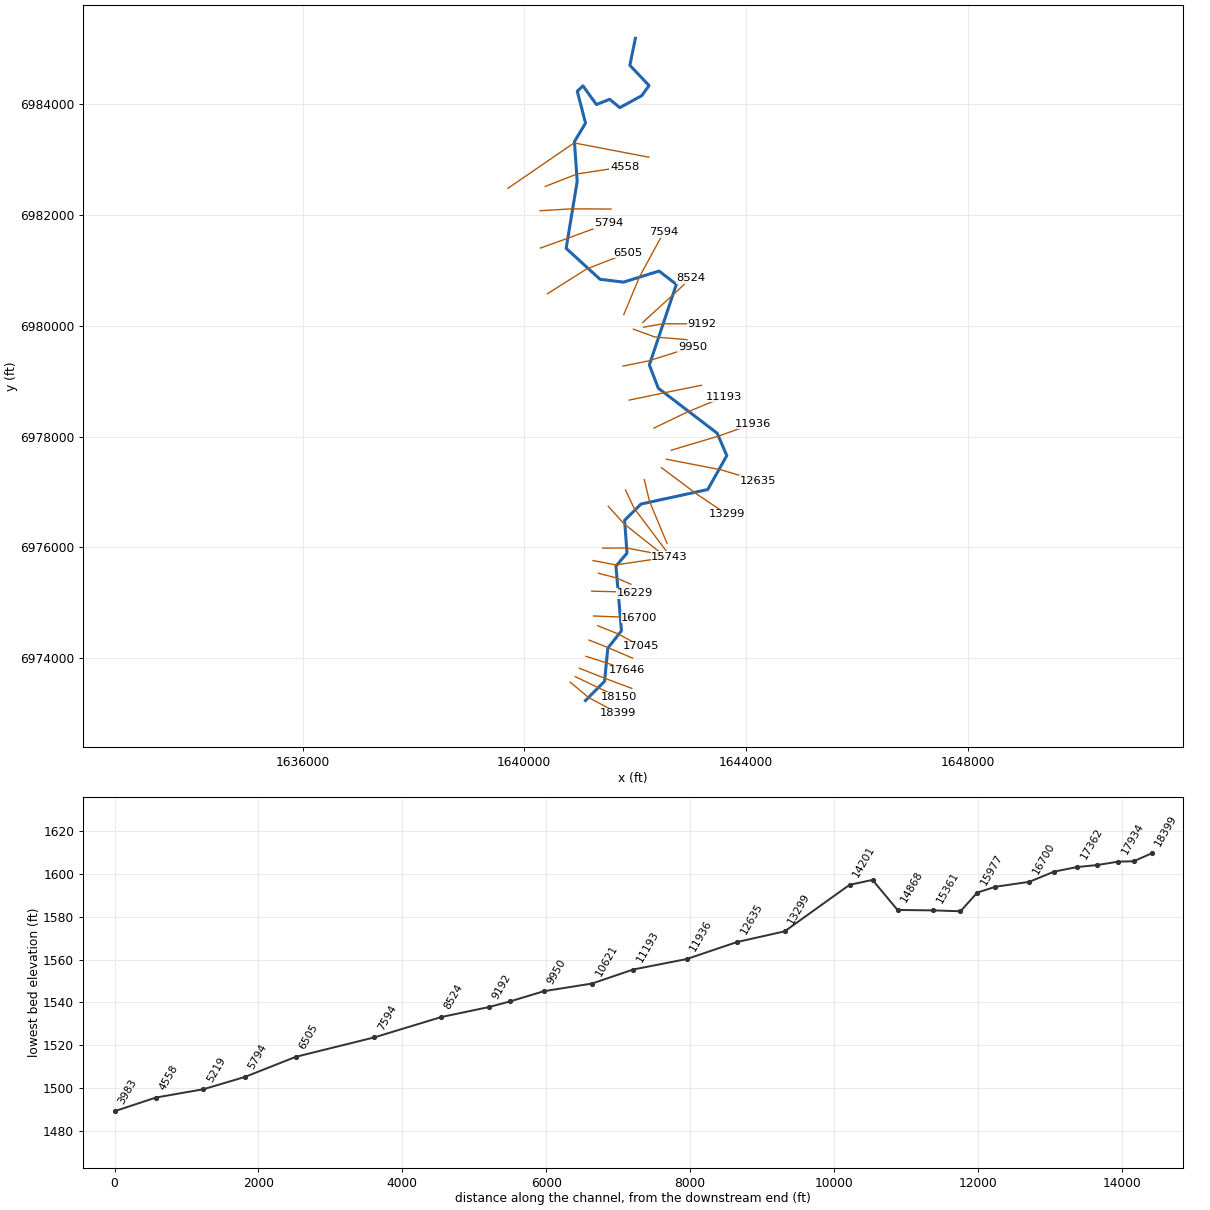
--- Chimney Creek 1136.prj (project) ---

Proj Title=Chimney Creek 1136 Base Level Engineering
Current Plan=p01
Default Exp/Contr=0.3,0.1
English Units
Geom File=g01
Flow File=f01
Plan File=p01
BEGIN DESCRIPTION:
Chimney Creek 1136
END DESCRIPTION:

--- Chimney Creek 1136.p01 (plan) ---

Plan Title=Multiple Run
Short Identifier=Multiple
Geom File=g01
Flow File=f01
Subcritical Flow
K Sum by GR= 0
Std Step Tol= 0.01
Critical Tol= 0.01
Num of Std Step Trials= 20
Max Error Tol= 0.3
Flow Tol Ratio= 0.001
Split Flow NTrial= 30
Split Flow Tol= 0.02
Split Flow Ratio= 0.02
Log Output Level= 0
Friction Slope Method= 1
Unsteady Friction Slope Method= 2
Unsteady Bridges Friction Slope Method= 1
Parabolic Critical Depth
Global Vel Dist=  1 , 1 , 1
Global Log Level= 0
CheckData=True
Encroach Param= -1, 0, 0, 0
BEGIN DESCRIPTION:
Multiple Run
END DESCRIPTION:

--- Chimney Creek 1136.f01 (steady flow) ---

Flow Title=Multiple
Number of Profiles=7
Profile Names=10-year,25-year,50-year,1pct_min,100-year,1pct_plu,500-year
River Rch & RM= Chimney Creek 11,Reach-1,18399
     220     300     366     222     444     885     660
River Rch & RM= Chimney Creek 11,Reach-1,17045
     376     530     660     409     816    1628    1262
River Rch & RM= Chimney Creek 11,Reach-1,14868
     516     741     933     584    1166    2326    1843
River Rch & RM= Chimney Creek 11,Reach-1,7594
     634     918    1164     733    1462    2917    2337
Boundary for River Rch & Prof#=Chimney Creek 11,Reach-1,1
Up Type=0
Dn Type=3
Dn Slope=0.005
Boundary for River Rch & Prof#=Chimney Creek 11,Reach-1,2
Up Type=0
Dn Type=3
Dn Slope=0.005
Boundary for River Rch & Prof#=Chimney Creek 11,Reach-1,3
Up Type=0
Dn Type=3
Dn Slope=0.005
Boundary for River Rch & Prof#=Chimney Creek 11,Reach-1,4
Up Type=0
Dn Type=3
Dn Slope=0.005
Boundary for River Rch & Prof#=Chimney Creek 11,Reach-1,5
Up Type=0
Dn Type=3
Dn Slope=0.005
Boundary for River Rch & Prof#=Chimney Creek 11,Reach-1,6
Up Type=0
Dn Type=3
Dn Slope=0.005
Boundary for River Rch & Prof#=Chimney Creek 11,Reach-1,7
Up Type=0
Dn Type=3
Dn Slope=0.005

--- Chimney Creek 1136.g01 (geometry) ---

Geom Title=Existing Conditions

River Reach=Chimney Creek 11,Reach-1
Reach XY= 30
      1641105.00      6973238.00      1641449.17      6973585.70
      1641507.24      6974182.07      1641753.95      6974498.43
      1641654.70      6975663.12      1641853.95      6975898.43
      1641810.84      6976490.29      1642106.58      6976784.17
      1643311.06      6977046.14      1643654.93      6977658.03
      1643481.82      6978061.70      1642418.40      6978874.70
      1642257.26      6979293.94      1642744.52      6980747.80
      1642432.31      6980988.11      1641791.08      6980788.68
      1641366.95      6980839.92      1640756.05      6981398.43
      1640954.93      6982608.03      1640905.40      6983324.09
      1641105.36      6983658.21      1640956.96      6984232.13
      1641058.22      6984330.17      1641302.29      6983993.28
      1641540.94      6984087.96      1641725.16      6983937.53
      1642121.68      6984154.64      1642251.90      6984336.35
      1641905.65      6984701.92      1642005.00      6985188.00

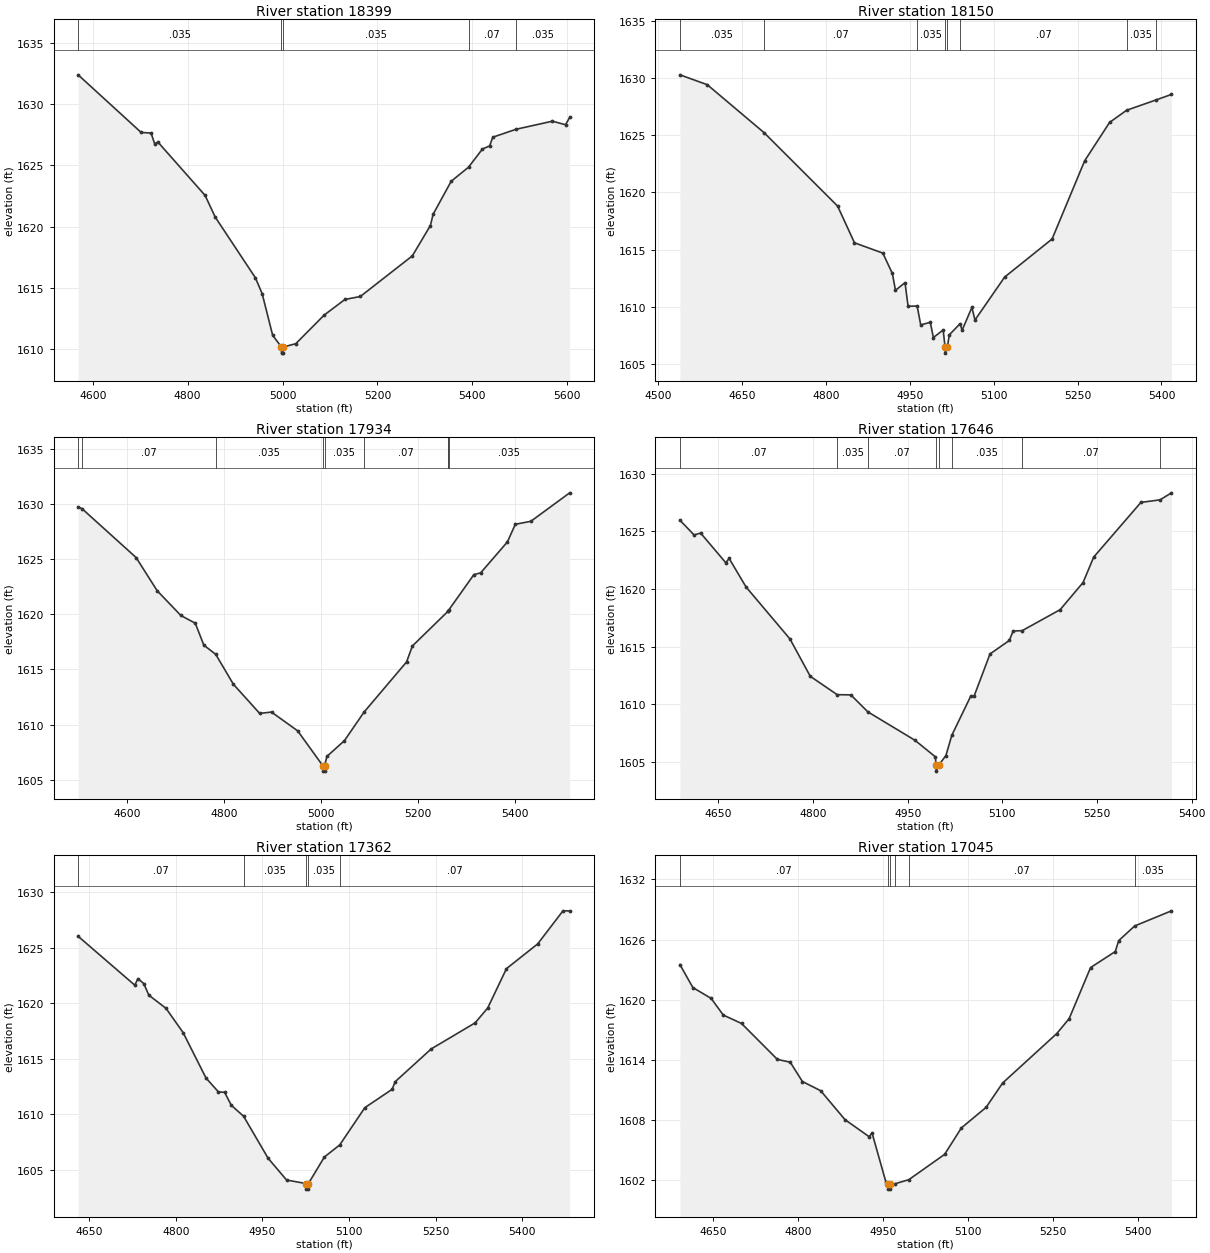
Type RM Length L Ch R = 1,18399,249,249,249
BEGIN DESCRIPTION:
Chimney Creek 1136 38.0
END DESCRIPTION:
XS GIS Cut Line= 3
      1640829.13      6973569.12      1641160.41      6973293.40
      1641693.69      6973006.63
#Sta/Elev= 30
  4569.0 1632.40  4701.9 1627.69  4722.8 1627.64  4730.6 1626.74  4737.1 1626.91
  4836.8 1622.54  4858.1 1620.77  4942.8 1615.81  4957.1 1614.51  4979.2 1611.11
  4997.7 1610.15  4998.0 1609.65  5001.5 1609.65  5001.7 1610.15  5027.9 1610.42
  5087.8 1612.76  5131.7 1614.04  5164.1 1614.28  5273.7 1617.60  5311.8 1620.08
  5317.5 1621.00  5355.7 1623.70  5392.2 1624.85  5421.4 1626.33  5436.7 1626.59
  5443.3 1627.30  5492.5 1627.95  5569.1 1628.61  5596.7 1628.32  5605.5 1628.92
#Mann=5,-1,0
  4569.0   0.035       0  4997.7   0.035       0  5001.7   0.035       0
  5392.2    0.07       0  5492.5   0.035       0
Bank Sta=4997.7,5001.7
Exp/Cntr=0.3,0.1

Type RM Length L Ch R = 1,18150,216,216,216
BEGIN DESCRIPTION:
Mapping XS 1c71aa20
END DESCRIPTION:
XS GIS Cut Line= 3
      1640920.97      6973669.78      1641330.65      6973471.88
      1641716.04      6973294.81
#Sta/Elev= 30
  4538.8 1630.27  4587.7 1629.41  4689.4 1625.22  4820.9 1618.81  4851.0 1615.61
  4901.7 1614.71  4918.8 1612.93  4924.3 1611.46  4941.4 1612.13  4946.9 1610.07
  4963.1 1610.09  4969.5 1608.44  4986.6 1608.67  4992.1 1607.34  5009.6 1608.00
  5013.1 1606.48  5013.3 1605.98  5017.1 1606.48  5020.6 1607.58  5039.9 1608.55
  5043.5 1607.98  5061.0 1609.97  5066.5 1608.87  5119.6 1612.62  5204.4 1615.94
  5262.7 1622.77  5307.3 1626.12  5337.8 1627.18  5389.9 1628.07  5417.9 1628.56
#Mann=8,-1,0
  4538.8   0.035       0  4689.4    0.07       0  4963.1   0.035       0
  5013.1   0.035       0  5017.1   0.035       0  5039.9    0.07       0
  5337.8   0.035       0  5389.9    0.07       0
Bank Sta=5013.1,5017.1
Exp/Cntr=0.3,0.1

Type RM Length L Ch R = 1,17934,288,288,288
BEGIN DESCRIPTION:
Mapping XS 37e1e0b4
END DESCRIPTION:
XS GIS Cut Line= 3
      1640993.82      6973820.85      1641457.39      6973638.55
      1641939.99      6973458.01
#Sta/Elev= 30
  4499.2 1629.73  4507.1 1629.57  4618.7 1625.14  4662.2 1622.13  4711.0 1619.89
  4740.7 1619.19  4758.4 1617.20  4782.9 1616.37  4819.3 1613.66  4873.5 1611.02
  4897.9 1611.14  4951.8 1609.44  5003.5 1606.29  5003.7 1605.79  5007.2 1605.79
  5007.5 1606.29  5012.0 1607.12  5048.2 1608.55  5088.7 1611.14  5176.3 1615.68
  5188.4 1617.13  5262.2 1620.29  5262.3 1620.30  5262.9 1620.36  5315.1 1623.59
  5329.1 1623.75  5384.3 1626.56  5400.5 1628.15  5432.5 1628.42  5512.6 1631.00
#Mann=9,-1,0
  4499.2   0.035       0  4507.1    0.07       0  4782.9   0.035       0
  5003.5   0.035       0  5007.5   0.035       0  5088.7    0.07       0
  5262.2   0.035       0  5262.3    0.07       0  5262.9   0.035       0
Bank Sta=5003.5,5007.5
Exp/Cntr=0.3,0.1

Type RM Length L Ch R = 1,17646,284,284,284
BEGIN DESCRIPTION:
Mapping XS 5749d331
END DESCRIPTION:
XS GIS Cut Line= 3
      1641113.67      6974036.11      1641504.26      6973911.12
      1641850.71      6973784.66
#Sta/Elev= 30
  4589.1 1625.98  4611.5 1624.70  4622.0 1624.86  4661.8 1622.29  4667.1 1622.66
  4694.0 1620.18  4763.5 1615.68  4795.7 1612.44  4838.3 1610.85  4860.0 1610.83
  4886.9 1609.36  4961.7 1606.89  4993.9 1605.46  4995.0 1604.72  4995.2 1604.22
  4999.0 1604.72  5010.6 1605.57  5019.9 1607.32  5050.0 1610.73  5055.3 1610.73
  5080.5 1614.38  5111.1 1615.55  5117.1 1616.37  5131.5 1616.40  5191.6 1618.22
  5227.9 1620.57  5244.8 1622.78  5319.6 1627.52  5349.9 1627.74  5368.0 1628.35
#Mann=8,-1,0
  4589.1    0.07       0  4838.3   0.035       0  4886.9    0.07       0
  4995.0    0.07       0  4999.0    0.07       0  5019.9   0.035       0
  5131.5    0.07       0  5349.9   0.035       0
Bank Sta=4995,4999
Exp/Cntr=0.3,0.1

Type RM Length L Ch R = 1,17362,317,317,317
BEGIN DESCRIPTION:
Mapping XS 3775d8fc
END DESCRIPTION:
XS GIS Cut Line= 3
      1641169.23      6974329.51      1641509.47      6974194.10
      1641955.63      6974003.14
#Sta/Elev= 30
  4630.7 1626.01  4728.9 1621.61  4734.3 1622.20  4744.5 1621.75  4753.2 1620.71
  4782.9 1619.53  4812.5 1617.35  4852.2 1613.26  4873.7 1612.01  4884.5 1611.97
  4896.1 1610.80  4917.3 1609.82  4959.8 1606.04  4991.8 1604.08  5025.6 1603.76
  5025.9 1603.26  5029.4 1603.26  5029.6 1603.76  5057.3 1606.15  5083.9 1607.24
  5127.4 1610.59  5174.6 1612.24  5180.0 1612.93  5242.2 1615.87  5318.4 1618.22
  5340.1 1619.55  5372.7 1623.10  5426.7 1625.32  5470.6 1628.30  5482.2 1628.29
#Mann=5,-1,0
  4630.7    0.07       0  4917.3   0.035       0  5025.6   0.035       0
  5029.6   0.035       0  5083.9    0.07       0
Bank Sta=5025.6,5029.6
Exp/Cntr=0.3,0.1

Type RM Length L Ch R = 1,17045,345,345,345
BEGIN DESCRIPTION:
Mapping XS 99a1a03e
END DESCRIPTION:
XS GIS Cut Line= 3
      1641323.67      6974588.21      1641695.23      6974440.63
      1642106.70      6974214.93
#Sta/Elev= 30
  4590.8 1623.51  4613.7 1621.22  4646.0 1620.14  4667.5 1618.48  4699.8 1617.64
  4763.2 1614.06  4785.9 1613.78  4807.4 1611.86  4839.7 1610.94  4882.7 1608.06
  4925.2 1606.37  4930.6 1606.72  4954.9 1601.87  4958.3 1601.64  4958.5 1601.14
  4962.0 1601.14  4962.3 1601.64  4970.9 1601.67  4995.5 1602.08  5058.8 1604.60
  5088.5 1607.24  5132.1 1609.28  5161.4 1611.71  5257.2 1616.64  5279.0 1618.12
  5316.9 1623.21  5360.5 1624.80  5366.7 1625.90  5394.8 1627.35  5459.9 1628.86
#Mann=6,-1,0
  4590.8    0.07       0  4958.3    0.07       0  4962.3    0.07       0
  4970.9   0.035       0  4995.5    0.07       0  5394.8   0.035       0
Bank Sta=4958.3,4962.3
Exp/Cntr=0.3,0.1

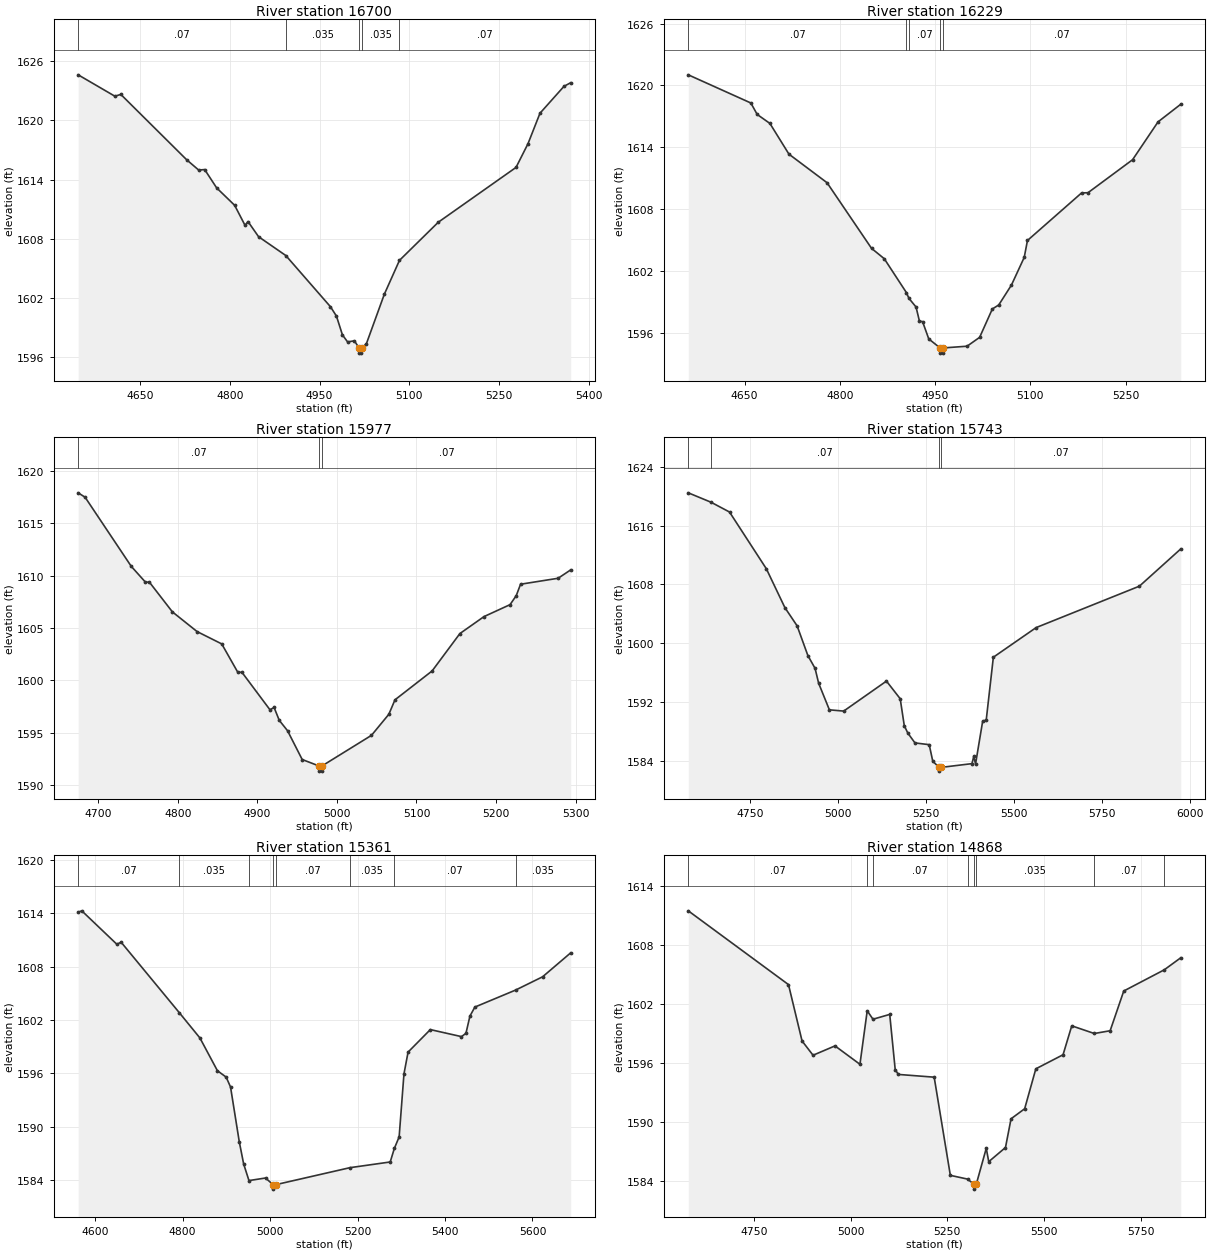
Type RM Length L Ch R = 1,16700,471,471,471
BEGIN DESCRIPTION:
Mapping XS efb97afe
END DESCRIPTION:
XS GIS Cut Line= 3
      1641253.73      6974763.75      1641707.27      6974746.39
      1642076.24      6974735.54
#Sta/Elev= 30
  4546.7 1624.63  4608.0 1622.46  4618.0 1622.64  4728.1 1616.00  4748.1 1614.96
  4758.1 1615.01  4778.1 1613.15  4808.2 1611.38  4825.5 1609.35  4830.5 1609.73
  4848.2 1608.19  4893.7 1606.28  4968.3 1601.08  4978.3 1600.13  4988.3 1598.22
  4996.9 1597.51  5008.3 1597.62  5016.3 1596.87  5016.6 1596.37  5020.1 1596.37
  5020.3 1596.87  5028.3 1597.32  5058.3 1602.35  5083.6 1605.79  5148.4 1609.66
  5278.4 1615.23  5298.4 1617.64  5318.4 1620.73  5358.5 1623.46  5369.7 1623.83
#Mann=5,-1,0
  4546.7    0.07       0  4893.7   0.035       0  5016.3   0.035       0
  5020.3   0.035       0  5083.6    0.07       0
Bank Sta=5016.3,5020.3
Exp/Cntr=0.3,0.1

Type RM Length L Ch R = 1,16229,252,252,252
BEGIN DESCRIPTION:
Mapping XS 61e03214
END DESCRIPTION:
XS GIS Cut Line= 3
      1641216.54      6975212.10      1641650.56      6975201.25
      1641990.65      6975173.09
#Sta/Elev= 30
  4561.4 1621.03  4659.9 1618.30  4669.9 1617.19  4689.9 1616.32  4719.9 1613.34
  4779.9 1610.57  4849.9 1604.21  4870.0 1603.20  4904.8 1599.92  4908.8 1599.36
  4920.0 1598.52  4925.3 1597.16  4930.3 1597.10  4940.0 1595.43  4957.9 1594.55
  4958.2 1594.05  4961.8 1594.05  4962.0 1594.55  5000.3 1594.72  5020.1 1595.58
  5040.1 1598.33  5050.2 1598.72  5070.2 1600.65  5090.3 1603.33  5095.4 1604.97
  5180.6 1609.58  5190.7 1609.60  5260.9 1612.80  5301.0 1616.47  5336.8 1618.18
#Mann=5,-1,0
  4561.4    0.07       0  4904.8   0.035       0  4908.8    0.07       0
  4957.9    0.07       0  4962.0    0.07       0
Bank Sta=4957.9,4962
Exp/Cntr=0.3,0.1

Type RM Length L Ch R = 1,15977,234,234,234
BEGIN DESCRIPTION:
Mapping XS ef35ac28
END DESCRIPTION:
XS GIS Cut Line= 3
      1641340.50      6975534.93      1641654.28      6975452.90
      1641925.10      6975337.02
#Sta/Elev= 30
  4674.9 1617.91  4683.6 1617.49  4741.6 1610.89  4759.3 1609.39  4764.5 1609.37
  4793.3 1606.54  4824.3 1604.66  4855.3 1603.48  4875.5 1600.77  4880.7 1600.77
  4915.9 1597.19  4921.1 1597.41  4927.6 1596.18  4938.0 1595.19  4956.4 1592.44
  4977.3 1591.83  4977.5 1591.33  4981.1 1591.33  4981.4 1591.83  5043.5 1594.75
  5065.3 1596.76  5073.0 1598.14  5119.7 1600.90  5154.6 1604.47  5184.9 1606.09
  5217.6 1607.23  5225.4 1608.09  5230.8 1609.18  5278.0 1609.75  5293.8 1610.55
#Mann=3,-1,0
  4674.9    0.07       0  4977.3    0.07       0  4981.4    0.07       0
Bank Sta=4977.3,4981.4
Exp/Cntr=0.3,0.1

Type RM Length L Ch R = 1,15743,382,382,382
BEGIN DESCRIPTION:
Mapping XS fad8c451
END DESCRIPTION:
XS GIS Cut Line= 3
      1641241.55      6975764.09      1641654.28      6975685.97
      1642621.11      6975828.89
#Sta/Elev= 30
  4575.6 1620.46  4640.2 1619.18  4692.6 1617.85  4797.2 1610.12  4849.6 1604.85
  4884.4 1602.36  4915.0 1598.31  4935.3 1596.58  4945.5 1594.55  4976.0 1590.93
  5016.6 1590.76  5137.9 1594.84  5176.9 1592.44  5188.5 1588.77  5198.6 1587.76
  5218.8 1586.43  5259.2 1586.19  5269.3 1583.94  5287.5 1583.09  5287.7 1582.59
  5291.6 1583.09  5380.5 1583.61  5385.6 1584.59  5390.7 1583.57  5410.8 1589.36
  5421.0 1589.55  5441.2 1598.09  5562.5 1602.12  5855.6 1607.76  5973.0 1612.83
#Mann=4,-1,0
  4575.6   0.035       0  4640.2    0.07       0  5287.5    0.07       0
  5291.6    0.07       0
Bank Sta=5287.5,5291.6
Exp/Cntr=0.3,0.1

Type RM Length L Ch R = 1,15361,493,493,493
BEGIN DESCRIPTION:
Mapping XS c51fa27a
END DESCRIPTION:
XS GIS Cut Line= 3
      1641416.69      6975988.58      1641850.72      6975990.75
      1642530.08      6975860.34
#Sta/Elev= 30
  4561.5 1614.12  4569.8 1614.27  4649.8 1610.52  4659.8 1610.74  4792.5 1602.84
  4839.8 1599.99  4879.8 1596.31  4899.8 1595.59  4909.8 1594.48  4929.8 1588.32
  4939.8 1585.83  4951.9 1583.97  4989.8 1584.26  5007.1 1583.51  5007.6 1583.01
  5013.0 1583.51  5182.8 1585.42  5274.8 1586.06  5284.2 1587.58  5295.2 1588.88
  5306.2 1595.95  5315.6 1598.40  5366.5 1600.93  5437.7 1600.14  5447.9 1600.51
  5457.0 1602.45  5468.3 1603.46  5561.4 1605.37  5623.1 1606.86  5687.3 1609.55
#Mann=8,-1,0
  4561.5    0.07       0  4792.5   0.035       0  4951.9    0.07       0
  5007.1    0.07       0  5013.0    0.07       0  5182.8   0.035       0
  5284.2    0.07       0  5561.4   0.035       0
Bank Sta=5007.1,5013
Exp/Cntr=0.3,0.1

Type RM Length L Ch R = 1,14868,348,348,348
BEGIN DESCRIPTION:
Mapping XS 7488cd42
END DESCRIPTION:
XS GIS Cut Line= 3
      1641515.33      6976744.21      1641799.20      6976429.09
      1642464.24      6975900.26
#Sta/Elev= 30
  4579.9 1611.49  4839.1 1603.99  4874.2 1598.26  4902.6 1596.81  4959.4 1597.76
  5023.9 1595.89  5042.7 1601.33  5057.6 1600.47  5100.9 1600.96  5115.1 1595.35
  5123.2 1594.86  5215.9 1594.58  5257.7 1584.60  5302.2 1584.22  5318.7 1583.70
  5319.2 1583.20  5324.8 1583.70  5350.6 1587.35  5357.0 1585.99  5400.3 1587.43
  5414.7 1590.35  5449.9 1591.37  5478.8 1595.43  5549.2 1596.86  5571.7 1599.80
  5630.0 1599.02  5671.0 1599.30  5706.2 1603.34  5810.8 1605.49  5853.7 1606.72
#Mann=8,-1,0
  4579.9    0.07       0  5042.7   0.035       0  5057.6    0.07       0
  5302.2   0.035       0  5318.7    0.07       0  5324.8   0.035       0
  5630.0    0.07       0  5810.8   0.035       0
Bank Sta=5318.7,5324.8
Exp/Cntr=0.3,0.1

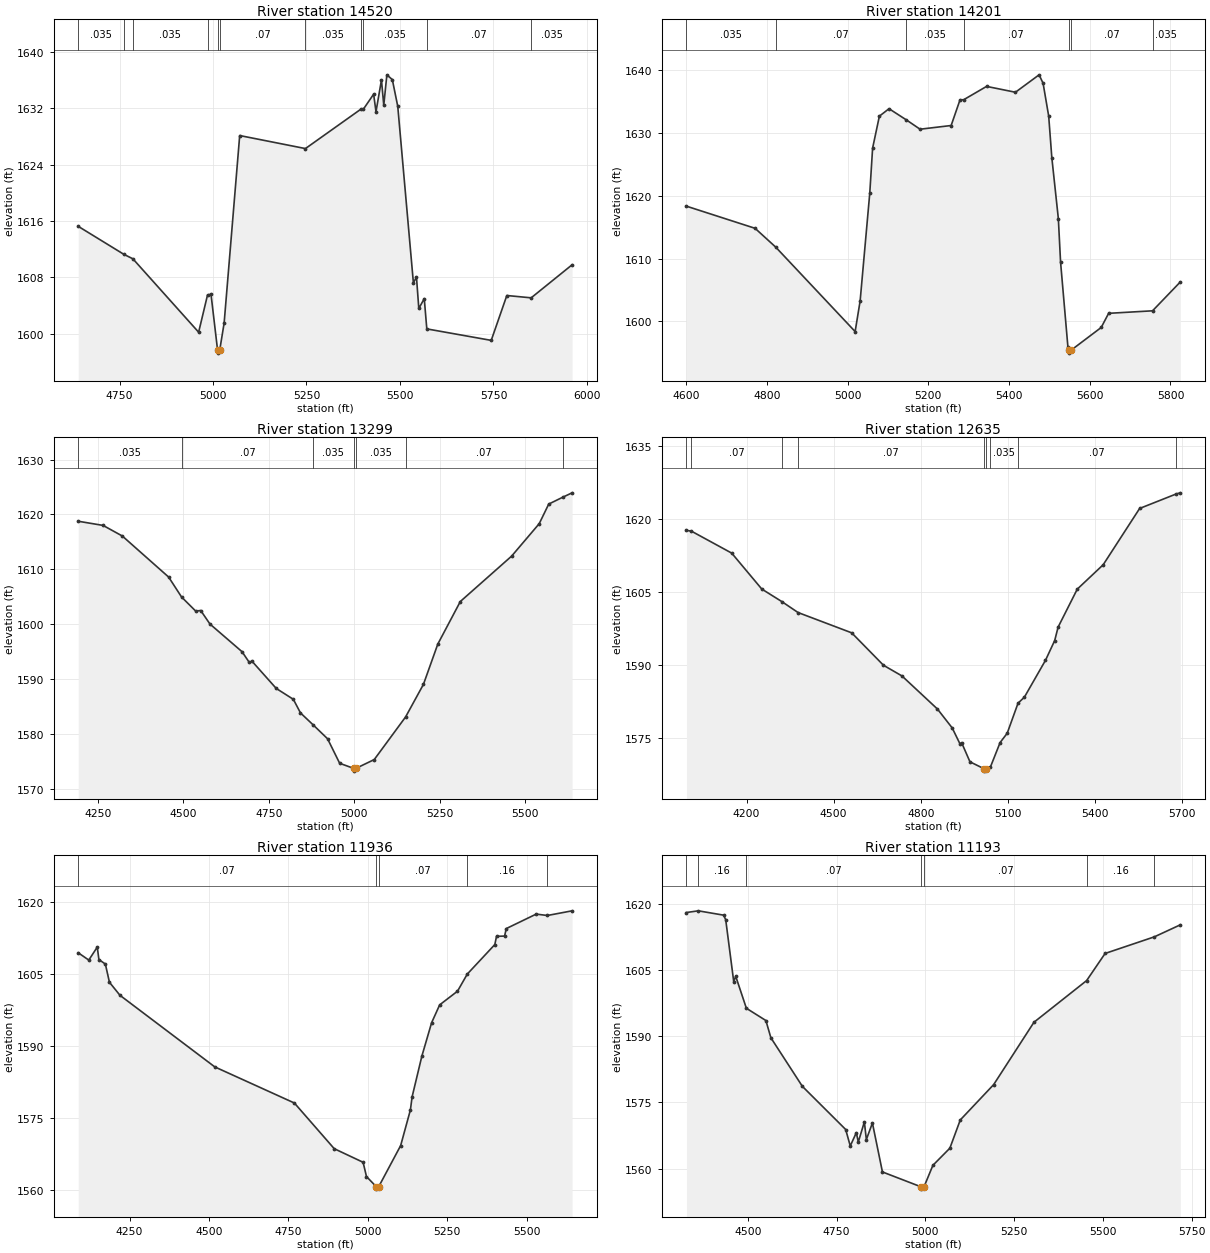
Type RM Length L Ch R = 1,14520,319,319,319
BEGIN DESCRIPTION:
Mapping XS 50735536
END DESCRIPTION:
XS GIS Cut Line= 3
      1641826.13      6977039.29      1641980.62      6976711.20
      1642556.28      6975945.38
#Sta/Elev= 30
  4639.6 1615.25  4761.8 1611.27  4785.8 1610.64  4961.6 1600.22  4985.4 1605.51
  4994.7 1605.60  5012.1 1597.75  5012.6 1597.25  5018.2 1597.75  5029.8 1601.52
  5071.4 1628.14  5247.2 1626.29  5394.6 1631.85  5401.6 1631.84  5429.6 1634.01
  5435.9 1631.52  5450.5 1636.03  5456.7 1632.44  5465.0 1636.76  5479.6 1636.08
  5494.1 1632.29  5535.9 1607.25  5544.2 1608.02  5550.4 1603.59  5565.0 1604.99
  5571.8 1600.69  5744.1 1599.06  5785.8 1605.43  5850.9 1605.10  5960.3 1609.79
#Mann=11,-1,0
  4639.6   0.035       0  4761.8    0.07       0  4785.8   0.035       0
  4985.4    0.07       0  5012.1    0.07       0  5018.2    0.07       0
  5247.2   0.035       0  5394.6    0.07       0  5401.6   0.035       0
  5571.8    0.07       0  5850.9   0.035       0
Bank Sta=5012.1,5018.2
Exp/Cntr=0.3,0.1

Type RM Length L Ch R = 1,14201,902,902,902
BEGIN DESCRIPTION:
Mapping XS 5d75320f
END DESCRIPTION:
XS GIS Cut Line= 3
      1642166.38      6977223.39      1642258.40      6976837.94
      1642576.10      6976074.06
#Sta/Elev= 30
  4600.8 1618.33  4770.8 1614.81  4821.9 1611.82  5018.7 1598.39  5031.1 1603.26
  5055.0 1620.43  5062.0 1627.56  5078.8 1632.65  5102.7 1633.83  5145.7 1632.05
  5179.6 1630.57  5256.6 1631.16  5278.6 1635.25  5287.4 1635.25  5344.4 1637.38
  5415.9 1636.45  5474.5 1639.22  5484.4 1637.88  5498.3 1632.65  5506.0 1626.07
  5522.2 1616.36  5527.7 1609.44  5546.0 1595.87  5548.4 1595.46  5548.9 1594.96
  5554.5 1595.46  5628.4 1599.04  5646.8 1601.29  5755.6 1601.69  5824.4 1606.28
#Mann=7,-1,0
  4600.8   0.035       0  4821.9    0.07       0  5145.7   0.035       0
  5287.4    0.07       0  5548.4    0.07       0  5554.5    0.07       0
  5755.6   0.035       0
Bank Sta=5548.4,5554.5
Exp/Cntr=0.3,0.1

Type RM Length L Ch R = 1,13299,664,664,664
BEGIN DESCRIPTION:
Mapping XS 31f677ba
END DESCRIPTION:
XS GIS Cut Line= 3
      1642476.15      6977439.71      1643118.47      6976960.57
      1643651.63      6976600.51
#Sta/Elev= 30
  4192.2 1618.75  4264.9 1617.99  4321.1 1616.06  4456.6 1608.58  4494.6 1604.93
  4535.9 1602.37  4550.5 1602.48  4577.6 1600.01  4671.4 1594.97  4692.2 1593.05
  4700.6 1593.23  4771.5 1588.27  4821.5 1586.29  4842.4 1583.81  4879.1 1581.65
  4921.6 1579.10  4957.0 1574.63  4998.0 1573.70  4998.5 1573.20  5004.5 1573.70
  5058.2 1575.31  5149.9 1583.08  5202.1 1589.02  5244.1 1596.36  5310.0 1604.12
  5460.0 1612.39  5540.8 1618.31  5568.6 1621.88  5609.3 1623.12  5636.9 1623.93
#Mann=7,-1,0
  4192.2   0.035       0  4494.6    0.07       0  4879.1   0.035       0
  4998.0   0.035       0  5004.5   0.035       0  5149.9    0.07       0
  5609.3   0.035       0
Bank Sta=4998,5004.5
Exp/Cntr=0.3,0.1

Type RM Length L Ch R = 1,12635,699,699,699
BEGIN DESCRIPTION:
Mapping XS b50cef86
END DESCRIPTION:
XS GIS Cut Line= 3
      1642566.40      6977592.51      1643552.50      6977401.54
      1644219.13      6977200.16
#Sta/Elev= 30
  3993.1 1617.64  4010.4 1617.46  4148.9 1612.96  4252.5 1605.58  4321.7 1603.00
  4377.3 1600.76  4562.1 1596.59  4671.6 1589.93  4735.2 1587.74  4857.5 1580.94
  4908.4 1577.05  4935.5 1573.73  4940.6 1574.05  4969.5 1570.10  5017.7 1568.69
  5018.2 1568.19  5024.3 1568.69  5039.4 1568.96  5073.3 1574.06  5097.8 1575.98
  5135.0 1582.14  5156.8 1583.37  5229.6 1590.95  5261.3 1595.01  5273.0 1597.76
  5339.0 1605.56  5428.4 1610.58  5553.8 1622.13  5679.9 1625.11  5693.9 1625.34
#Mann=9,-1,0
  3993.1   0.035       0  4010.4    0.07       0  4321.7   0.035       0
  4377.3    0.07       0  5017.7    0.07       0  5024.3    0.07       0
  5039.4   0.035       0  5135.0    0.07       0  5679.9   0.035       0
Bank Sta=5017.7,5024.3
Exp/Cntr=0.3,0.1

Type RM Length L Ch R = 1,11936,743,743,743
BEGIN DESCRIPTION:
Mapping XS 3ae5dc2f
END DESCRIPTION:
XS GIS Cut Line= 3
      1642653.16      6977755.70      1643524.72      6978016.12
      1644131.18      6978234.45
#Sta/Elev= 30
  4088.6 1609.38  4121.8 1607.86  4148.5 1610.56  4153.7 1607.97  4174.0 1607.03
  4186.8 1603.25  4219.9 1600.54  4518.4 1585.65  4768.9 1578.14  4894.2 1568.65
  4985.1 1565.82  4995.8 1562.85  5026.7 1560.74  5027.2 1560.24  5034.2 1560.74
  5103.3 1569.29  5134.0 1576.71  5139.3 1579.41  5170.0 1587.88  5200.7 1594.83
  5226.1 1598.55  5282.2 1601.39  5313.0 1604.95  5399.7 1611.09  5405.0 1612.80
  5430.4 1612.85  5435.7 1614.41  5529.9 1617.42  5565.0 1617.13  5642.8 1618.10
#Mann=5,-1,0
  4088.6    0.07       0  5026.7    0.07       0  5034.2    0.07       0
  5313.0    0.16       0  5565.0   0.035       0
Bank Sta=5026.7,5034.2
Exp/Cntr=0.3,0.1

Type RM Length L Ch R = 1,11193,572,572,572
BEGIN DESCRIPTION:
Mapping XS ab76559f
END DESCRIPTION:
XS GIS Cut Line= 3
      1642340.72      6978155.03      1642948.33      6978446.68
      1643610.72      6978720.65
#Sta/Elev= 30
  4327.4 1617.98  4360.8 1618.36  4432.0 1617.38  4437.9 1616.36  4460.5 1602.33
  4466.1 1603.54  4496.1 1596.30  4551.1 1593.52  4565.1 1589.62  4653.8 1578.62
  4775.8 1568.85  4788.7 1565.12  4805.8 1568.14  4811.3 1566.01  4828.4 1570.56
  4834.0 1566.58  4851.1 1570.32  4879.3 1559.24  4988.7 1555.85  4989.2 1555.35
  4996.3 1555.85  5021.4 1560.74  5069.2 1564.62  5098.5 1571.01  5192.6 1579.02
  5306.0 1593.13  5454.4 1602.57  5506.4 1608.71  5645.1 1612.47  5718.2 1615.19
#Mann=7,-1,0
  4327.4    0.07       0  4360.8    0.16       0  4496.1    0.07       0
  4988.7    0.07       0  4996.3    0.07       0  5454.4    0.16       0
  5645.1    0.07       0
Bank Sta=4988.7,4996.3
Exp/Cntr=0.3,0.1

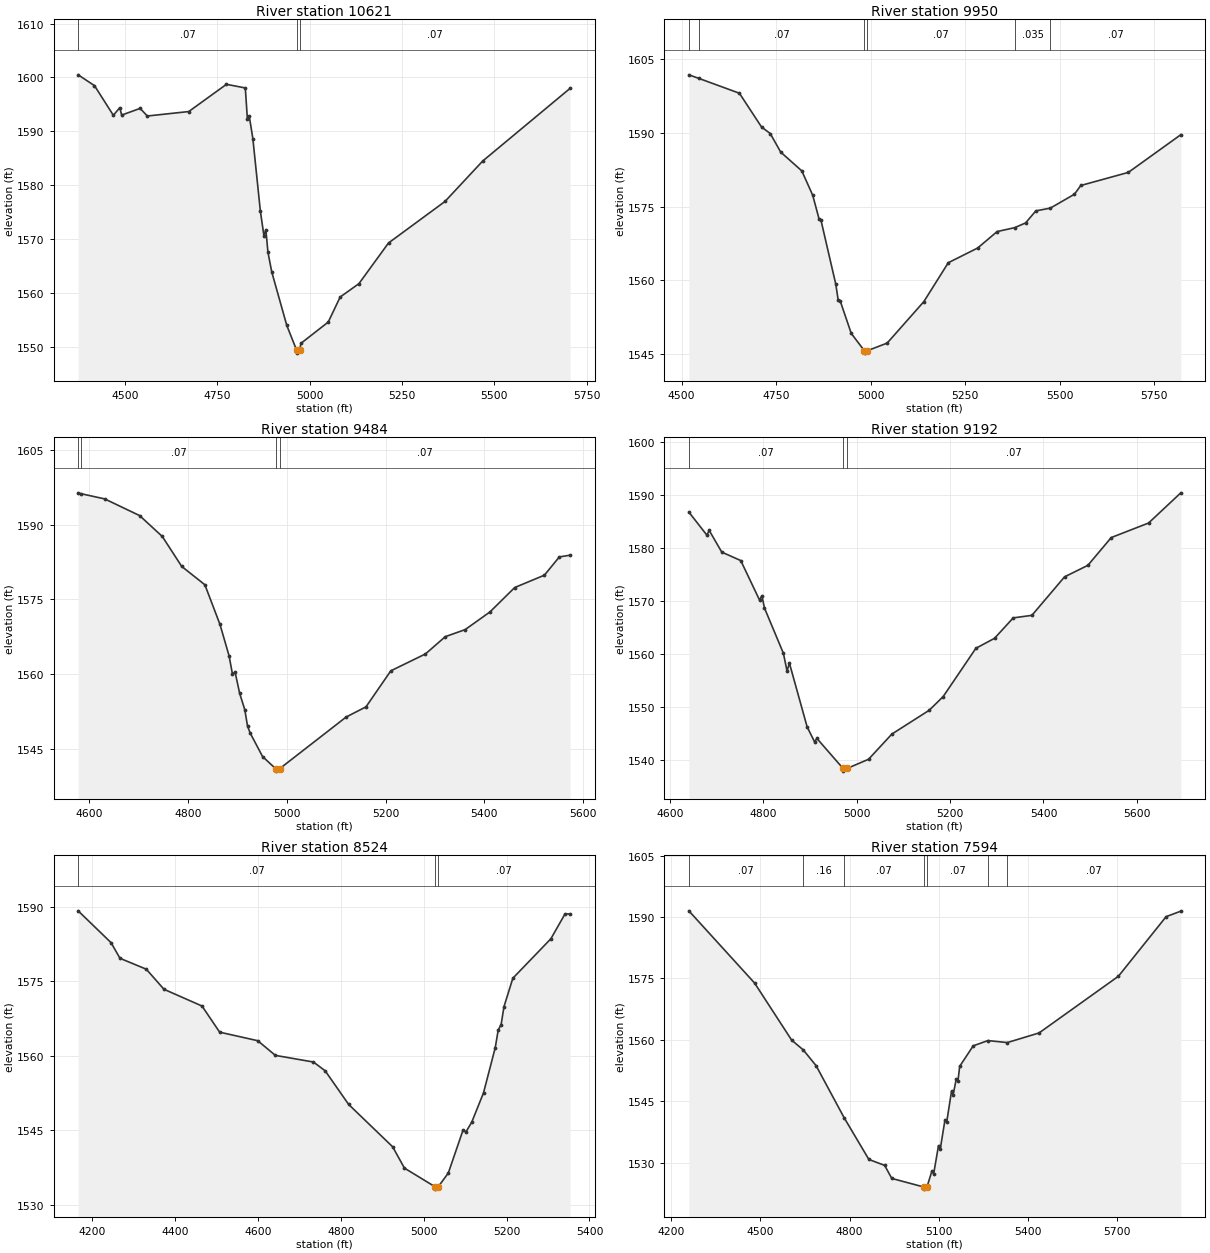
Type RM Length L Ch R = 1,10621,671,671,671
BEGIN DESCRIPTION:
Mapping XS 25b9b119
END DESCRIPTION:
XS GIS Cut Line= 3
      1641891.60      6978659.64      1642509.67      6978788.11
      1643197.20      6978927.01
#Sta/Elev= 30
  4372.8 1600.48  4417.1 1598.47  4468.2 1592.96  4485.6 1594.38  4490.7 1593.00
  4540.8 1594.25  4560.1 1592.83  4672.5 1593.66  4774.6 1598.72  4825.7 1598.04
  4831.2 1592.34  4836.3 1592.82  4846.1 1588.64  4866.5 1575.12  4876.2 1570.56
  4881.3 1571.71  4887.0 1567.53  4897.2 1563.89  4938.0 1553.94  4964.9 1549.29
  4965.4 1548.79  4972.5 1549.29  4976.4 1550.61  5050.3 1554.56  5082.6 1559.21
  5133.4 1561.69  5213.6 1569.25  5366.6 1576.96  5468.6 1584.46  5705.5 1597.97
#Mann=3,-1,0
  4372.8    0.07       0  4964.9    0.07       0  4972.5    0.07       0
Bank Sta=4964.9,4972.5
Exp/Cntr=0.3,0.1

Type RM Length L Ch R = 1,9950,466,466,466
BEGIN DESCRIPTION:
Mapping XS 8be625cb
END DESCRIPTION:
XS GIS Cut Line= 3
      1641783.97      6979274.22      1642245.78      6979367.98
      1643037.42      6979617.96
#Sta/Elev= 30
  4519.3 1601.78  4545.2 1601.07  4653.0 1598.04  4711.7 1591.16  4734.6 1589.85
  4762.3 1586.07  4818.1 1582.25  4846.9 1577.31  4863.6 1572.52  4868.7 1572.25
  4908.1 1559.17  4914.2 1556.04  4919.3 1555.89  4948.9 1549.21  4983.5 1545.70
  4984.0 1545.20  4991.7 1545.70  5043.9 1547.24  5140.9 1555.67  5205.6 1563.58
  5283.3 1566.57  5334.9 1569.92  5380.9 1570.70  5410.1 1571.67  5437.2 1574.12
  5475.5 1574.68  5539.4 1577.51  5556.0 1579.28  5681.8 1581.94  5820.7 1589.61
#Mann=6,-1,0
  4519.3   0.035       0  4545.2    0.07       0  4983.5    0.07       0
  4991.7    0.07       0  5380.9   0.035       0  5475.5    0.07       0
Bank Sta=4983.5,4991.7
Exp/Cntr=0.3,0.1

Type RM Length L Ch R = 1,9484,292,292,292
BEGIN DESCRIPTION:
Mapping XS 7a163efb
END DESCRIPTION:
XS GIS Cut Line= 3
      1641968.04      6979940.88      1642356.89      6979798.53
      1642936.77      6979749.92
#Sta/Elev= 30
  4577.7 1596.42  4583.7 1596.24  4631.4 1595.20  4702.2 1591.84  4748.1 1587.64
  4787.4 1581.62  4834.3 1577.93  4864.9 1569.94  4883.3 1563.63  4890.1 1559.98
  4895.4 1560.40  4904.6 1556.14  4915.2 1552.76  4920.6 1549.53  4925.9 1548.13
  4951.1 1543.38  4977.5 1540.95  4978.0 1540.45  4985.8 1540.95  5120.3 1551.33
  5160.5 1553.38  5210.7 1560.62  5280.9 1564.02  5321.0 1567.49  5361.2 1568.91
  5411.4 1572.46  5461.5 1577.37  5521.7 1579.86  5551.9 1583.53  5573.7 1583.88
#Mann=4,-1,0
  4577.7    0.16       0  4583.7    0.07       0  4977.5    0.07       0
  4985.8    0.07       0
Bank Sta=4977.5,4985.8
Exp/Cntr=0.3,0.1

Type RM Length L Ch R = 1,9192,668,668,668
BEGIN DESCRIPTION:
Mapping XS 7e0311ad
END DESCRIPTION:
XS GIS Cut Line= 3
      1642155.55      6979975.62      1642506.20      6980038.11
      1643204.11      6980034.64
#Sta/Elev= 30
  4640.2 1586.82  4678.7 1582.47  4683.8 1583.35  4710.7 1579.25  4751.4 1577.65
  4791.6 1570.19  4796.7 1570.99  4802.2 1568.68  4842.8 1560.11  4850.6 1556.75
  4855.6 1558.27  4893.6 1546.20  4909.5 1543.38  4914.6 1544.01  4970.7 1538.33
  4971.2 1537.83  4979.0 1538.33  5025.2 1540.07  5075.2 1544.84  5155.2 1549.34
  5185.2 1551.94  5255.2 1561.06  5295.2 1562.95  5335.2 1566.81  5375.2 1567.29
  5445.2 1574.57  5495.2 1576.75  5545.2 1582.00  5625.2 1584.75  5694.3 1590.46
#Mann=3,-1,0
  4640.2    0.07       0  4970.7    0.07       0  4979.0    0.07       0
Bank Sta=4970.7,4979
Exp/Cntr=0.3,0.1

Type RM Length L Ch R = 1,8524,930,930,930
BEGIN DESCRIPTION:
Mapping XS a66cbb75
END DESCRIPTION:
XS GIS Cut Line= 5
      1642138.12      6980062.40      1642756.20      6980624.92
      1643002.73      6980861.03      1643009.67      6980861.03
      1643009.67      6980857.57
#Sta/Elev= 30
  4165.8 1589.21  4245.2 1582.80  4266.8 1579.64  4330.4 1577.44  4372.9 1573.40
  4464.8 1570.02  4507.4 1564.75  4599.3 1563.03  4641.9 1560.07  4733.8 1558.73
  4762.1 1556.96  4818.9 1550.17  4925.0 1541.64  4953.4 1537.35  5026.9 1533.61
  5027.4 1533.11  5035.3 1533.61  5059.4 1536.37  5094.9 1545.02  5101.8 1544.62
  5116.0 1546.63  5144.3 1552.52  5172.6 1561.62  5179.8 1565.20  5186.8 1566.28
  5193.7 1569.89  5215.1 1575.62  5306.9 1583.58  5341.0 1588.58  5353.3 1588.58
#Mann=3,-1,0
  4165.8    0.07       0  5026.9    0.07       0  5035.3    0.07       0
Bank Sta=5026.9,5035.3
Exp/Cntr=0.3,0.1

Type RM Length L Ch R = 1,7594,1089,1089,1089
BEGIN DESCRIPTION:
Mapping XS 061b247e
END DESCRIPTION:
XS GIS Cut Line= 3
      1641796.85      6980204.45      1642083.31      6980891.96
      1642518.20      6981691.43
#Sta/Elev= 30
  4259.5 1591.51  4480.6 1573.89  4605.1 1559.98  4644.5 1557.56  4687.5 1553.73
  4781.7 1541.04  4865.1 1530.84  4918.2 1529.39  4942.1 1526.21  5050.7 1524.10
  5051.2 1523.60  5060.4 1524.10  5077.4 1528.08  5083.1 1527.37  5099.3 1534.22
  5105.0 1533.29  5121.1 1540.51  5126.8 1539.93  5143.0 1547.46  5148.7 1546.68
  5159.1 1550.49  5164.8 1550.05  5170.6 1553.57  5216.1 1558.57  5265.6 1559.85
  5330.7 1559.36  5437.5 1561.71  5704.4 1575.54  5865.0 1590.09  5914.4 1591.43
#Mann=7,-1,0
  4259.5    0.07       0  4644.5    0.16       0  4781.7    0.07       0
  5050.7    0.07       0  5060.4    0.07       0  5265.6    0.16       0
  5330.7    0.07       0
Bank Sta=5050.7,5060.4
Exp/Cntr=0.3,0.1

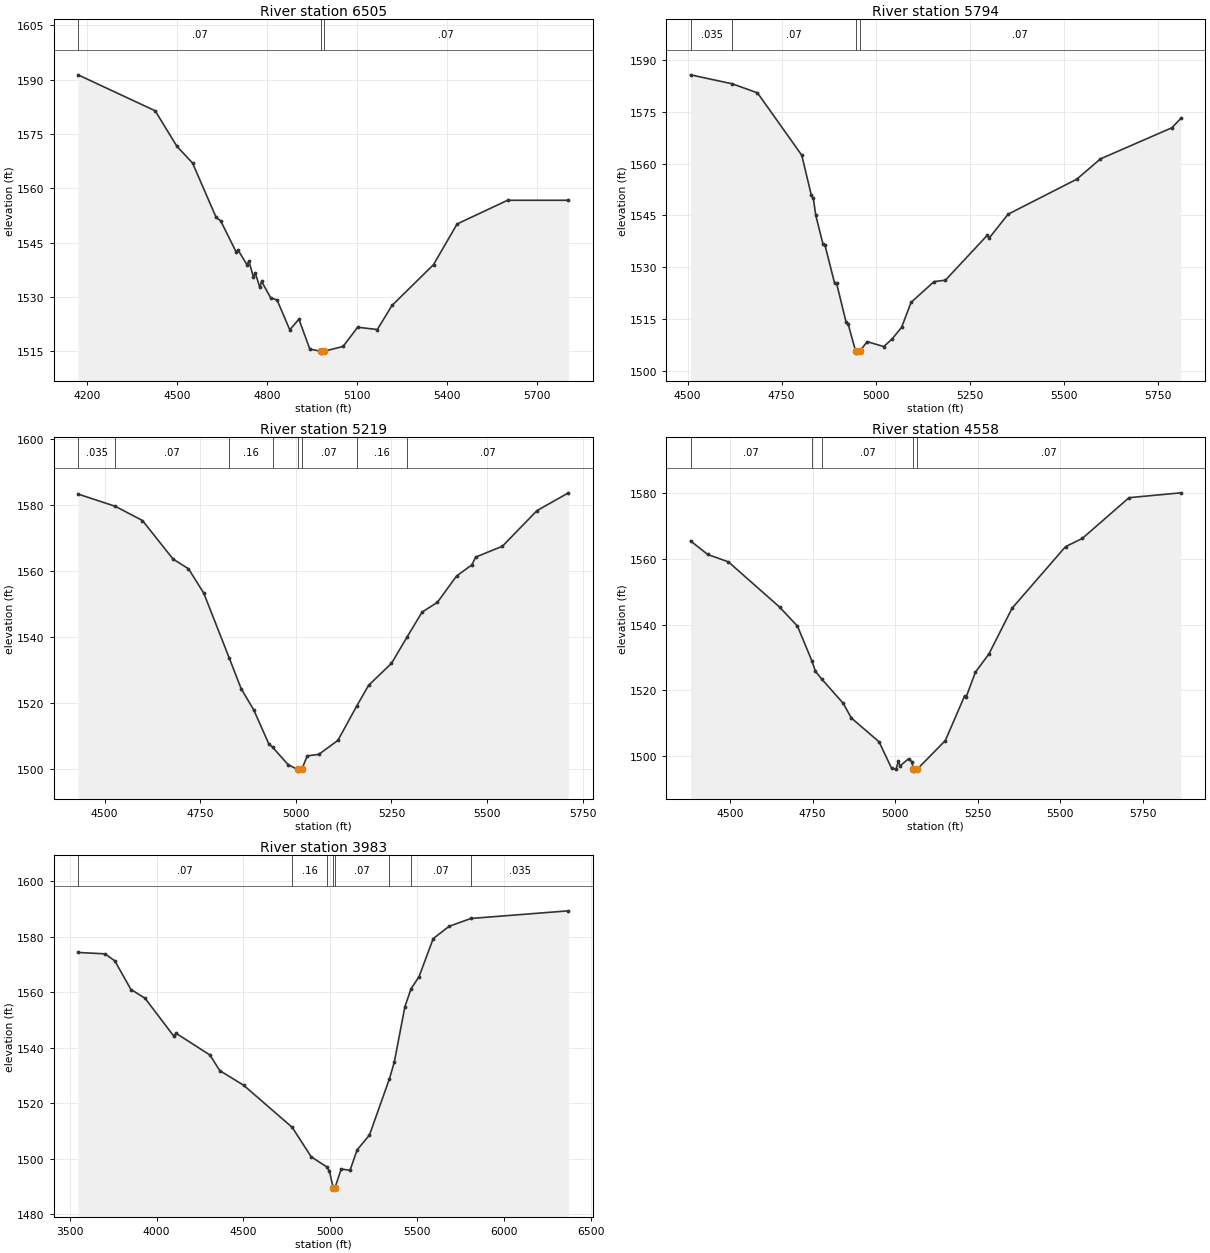
Type RM Length L Ch R = 1,6505,711,711,711
BEGIN DESCRIPTION:
Mapping XS 27e8b27c
END DESCRIPTION:
XS GIS Cut Line= 3
      1640417.52      6980578.59      1641124.98      6981025.64
      1641870.73      6981316.13
#Sta/Elev= 30
  4168.7 1591.32  4426.1 1581.40  4499.0 1571.57  4550.8 1567.00  4629.6 1552.01
  4644.9 1551.03  4696.6 1542.43  4702.5 1543.04  4733.1 1538.87  4739.0 1539.97
  4754.3 1535.50  4760.2 1536.71  4775.5 1532.67  4781.4 1534.35  4811.9 1529.77
  4833.1 1529.21  4875.5 1520.97  4906.0 1523.90  4942.5 1515.66  4979.7 1515.04
  4980.2 1514.54  4990.0 1515.04  5053.6 1516.39  5102.2 1521.69  5167.8 1521.05
  5216.8 1527.69  5355.4 1538.95  5434.3 1550.18  5602.8 1556.71  5805.9 1556.71
#Mann=3,-1,0
  4168.7    0.07       0  4979.7    0.07       0  4990.0    0.07       0
Bank Sta=4979.7,4990
Exp/Cntr=0.3,0.1

Type RM Length L Ch R = 1,5794,575,575,575
BEGIN DESCRIPTION:
Mapping XS be3b5430
END DESCRIPTION:
XS GIS Cut Line= 3
      1640291.68      6981403.25      1640751.72      6981568.17
      1641515.58      6981850.28
#Sta/Elev= 30
  4507.8 1585.74  4619.0 1583.13  4685.7 1580.51  4803.4 1562.45  4828.9 1550.80
  4834.2 1549.94  4840.6 1545.04  4859.6 1536.75  4864.9 1536.45  4890.4 1525.46
  4895.7 1525.42  4921.1 1514.09  4926.4 1513.60  4946.7 1505.59  4947.2 1505.09
  4957.1 1505.59  4977.3 1508.42  5021.3 1506.98  5043.6 1509.22  5068.7 1512.57
  5093.8 1519.79  5154.7 1525.81  5185.1 1526.23  5296.1 1539.21  5301.5 1538.44
  5351.6 1545.35  5534.2 1555.50  5597.0 1561.38  5786.7 1570.39  5810.8 1573.14
#Mann=4,-1,0
  4507.8   0.035       0  4619.0    0.07       0  4946.7    0.07       0
  4957.1    0.07       0
Bank Sta=4946.7,4957.1
Exp/Cntr=0.3,0.1

Type RM Length L Ch R = 1,5219,661,661,661
BEGIN DESCRIPTION:
Mapping XS 8811b45e
END DESCRIPTION:
XS GIS Cut Line= 3
      1640286.99      6982076.85      1640855.59      6982111.57
      1641567.41      6982107.23
#Sta/Elev= 30
  4430.9 1583.31  4528.3 1579.59  4599.2 1575.29  4679.4 1563.59  4719.5 1560.68
  4759.5 1553.27  4825.5 1533.78  4857.3 1524.29  4889.8 1517.96  4929.8 1507.52
  4939.1 1506.64  4979.9 1501.31  5004.8 1499.86  5005.3 1499.36  5015.2 1499.86
  5030.0 1503.99  5060.0 1504.43  5110.0 1508.69  5158.7 1518.99  5190.0 1525.34
  5250.0 1532.02  5290.0 1539.86  5330.0 1547.55  5370.0 1550.51  5420.0 1558.47
  5460.0 1561.86  5470.0 1564.21  5540.0 1567.51  5630.0 1578.27  5712.4 1583.68
#Mann=8,-1,0
  4430.9   0.035       0  4528.3    0.07       0  4825.5    0.16       0
  4939.1    0.07       0  5004.8    0.07       0  5015.2    0.07       0
  5158.7    0.16       0  5290.0    0.07       0
Bank Sta=5004.8,5015.2
Exp/Cntr=0.3,0.1

Type RM Length L Ch R = 1,4558,575,575,575
BEGIN DESCRIPTION:
Mapping XS d8511941
END DESCRIPTION:
XS GIS Cut Line= 3
      1640378.15      6982515.22      1640955.42      6982740.91
      1641810.25      6982871.09
#Sta/Elev= 30
  4380.6 1565.39  4432.9 1561.26  4495.3 1559.02  4650.1 1545.31  4704.4 1539.50
  4747.7 1529.04  4758.7 1525.80  4777.6 1523.46  4842.8 1516.08  4867.3 1511.62
  4951.4 1504.37  4989.2 1496.35  5002.7 1495.99  5009.7 1498.49  5014.7 1497.06
  5040.5 1499.21  5050.6 1498.38  5055.4 1495.97  5055.9 1495.47  5066.0 1495.97
  5152.0 1504.76  5210.5 1518.37  5215.5 1518.11  5242.8 1525.47  5284.1 1531.09
  5354.0 1544.94  5515.9 1563.65  5566.4 1566.12  5708.1 1578.52  5865.1 1579.99
#Mann=5,-1,0
  4380.6    0.07       0  4747.7    0.16       0  4777.6    0.07       0
  5055.4    0.07       0  5066.0    0.07       0
Bank Sta=5055.4,5066
Exp/Cntr=0.3,0.1

Type RM Length L Ch R = 1,3983,0,0,0
BEGIN DESCRIPTION:
Mapping XS bc799c4e
END DESCRIPTION:
XS GIS Cut Line= 3
      1639706.39      6982482.81      1640899.00      6983300.81
      1642248.99      6983042.85
#Sta/Elev= 30
  3548.5 1574.34  3703.2 1573.84  3760.0 1571.32  3852.7 1560.99  3933.3 1557.88
  4097.7 1544.31  4112.6 1545.21  4306.9 1537.40  4363.7 1531.78  4501.1 1526.49
  4780.3 1511.33  4889.6 1500.72  4978.7 1497.10  4994.7 1495.49  5015.8 1489.57
  5016.3 1489.07  5026.5 1489.57  5061.9 1496.33  5112.8 1495.85  5153.5 1503.17
  5224.8 1508.59  5339.5 1528.83  5367.3 1534.78  5428.4 1554.80  5463.7 1561.26
  5509.8 1565.63  5591.3 1579.33  5682.9 1583.77  5808.3 1586.59  6369.1 1589.34
#Mann=8,-1,0
  3548.5    0.07       0  4780.3    0.16       0  4978.7    0.07       0
  5015.8    0.07       0  5026.5    0.07       0  5339.5    0.16       0
  5463.7    0.07       0  5808.3   0.035       0
Bank Sta=5015.8,5026.5
Exp/Cntr=0.3,0.1

Chan Stop Cuts=-1