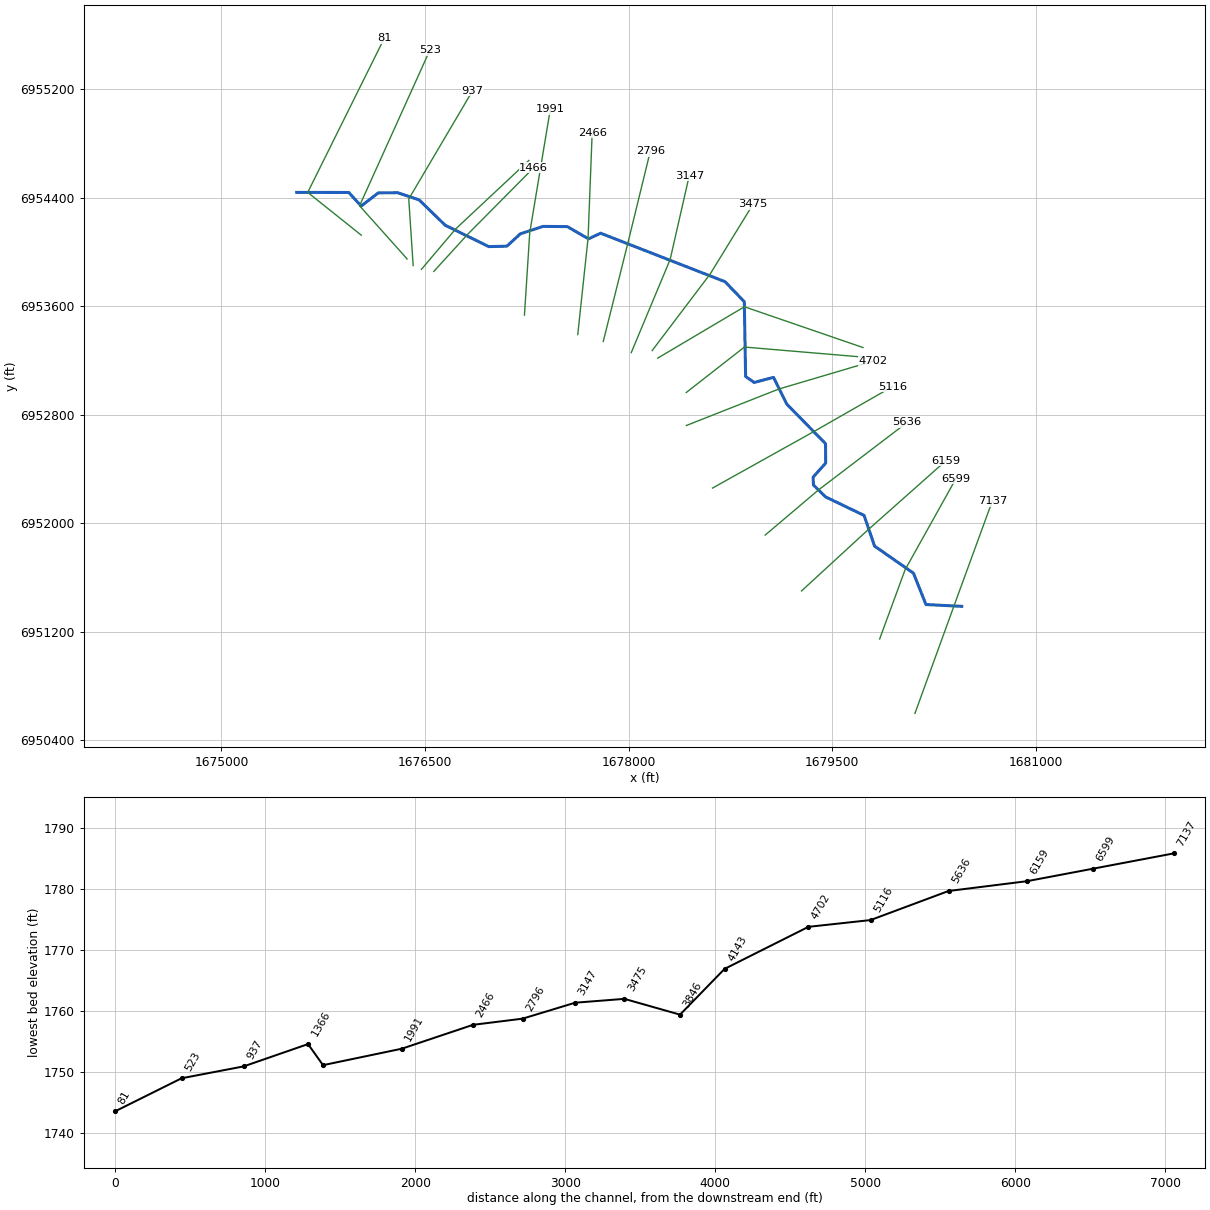
--- Chimney Creek 1137.prj (project) ---

Proj Title=Chimney Creek 1137 Base Level Engineering
Current Plan=p01
Default Exp/Contr=0.3,0.1
English Units
Geom File=g01
Flow File=f01
Plan File=p01
BEGIN DESCRIPTION:
Chimney Creek 1137
END DESCRIPTION:

--- Chimney Creek 1137.p01 (plan) ---

Plan Title=Multiple Run
Short Identifier=Multiple
Geom File=g01
Flow File=f01
Subcritical Flow
K Sum by GR= 0
Std Step Tol= 0.01
Critical Tol= 0.01
Num of Std Step Trials= 20
Max Error Tol= 0.3
Flow Tol Ratio= 0.001
Split Flow NTrial= 30
Split Flow Tol= 0.02
Split Flow Ratio= 0.02
Log Output Level= 0
Friction Slope Method= 1
Unsteady Friction Slope Method= 2
Unsteady Bridges Friction Slope Method= 1
Parabolic Critical Depth
Global Vel Dist=  1 , 1 , 1
Global Log Level= 0
CheckData=True
Encroach Param= -1, 0, 0, 0
BEGIN DESCRIPTION:
Multiple Run
END DESCRIPTION:

--- Chimney Creek 1137.f01 (steady flow) ---

Flow Title=Multiple
Number of Profiles=7
Profile Names=10-year,25-year,50-year,1pct_min,100-year,1pct_plu,500-year
River Rch & RM= Chimney Creek 11,Reach-1,7137
     261     361     444     272     543    1083     822
River Rch & RM= Chimney Creek 11,Reach-1,6159
     273     378     465     285     568    1133     858
River Rch & RM= Chimney Creek 11,Reach-1,3475
     447     632     789     490     978    1950    1518
Boundary for River Rch & Prof#=Chimney Creek 11,Reach-1,1
Up Type=0
Dn Type=3
Dn Slope=0.005
Boundary for River Rch & Prof#=Chimney Creek 11,Reach-1,2
Up Type=0
Dn Type=3
Dn Slope=0.005
Boundary for River Rch & Prof#=Chimney Creek 11,Reach-1,3
Up Type=0
Dn Type=3
Dn Slope=0.005
Boundary for River Rch & Prof#=Chimney Creek 11,Reach-1,4
Up Type=0
Dn Type=3
Dn Slope=0.005
Boundary for River Rch & Prof#=Chimney Creek 11,Reach-1,5
Up Type=0
Dn Type=3
Dn Slope=0.005
Boundary for River Rch & Prof#=Chimney Creek 11,Reach-1,6
Up Type=0
Dn Type=3
Dn Slope=0.005
Boundary for River Rch & Prof#=Chimney Creek 11,Reach-1,7
Up Type=0
Dn Type=3
Dn Slope=0.005

--- Chimney Creek 1137.g01 (geometry) ---

Geom Title=Existing Conditions

River Reach=Chimney Creek 11,Reach-1
Reach XY= 30
      1680455.00      6951388.00      1680191.27      6951401.20
      1680099.41      6951632.39      1679812.87      6951831.86
      1679735.39      6952058.18      1679452.68      6952193.82
      1679362.45      6952281.93      1679360.08      6952340.28
      1679452.83      6952443.45      1679451.47      6952586.53
      1679165.76      6952878.32      1679068.57      6953075.02
      1678925.02      6953037.56      1678862.69      6953081.43
      1678853.00      6953632.63      1678711.08      6953779.91
      1677794.29      6954137.18      1677705.00      6954095.56
      1677549.07      6954185.76      1677370.22      6954187.48
      1677202.58      6954132.46      1677103.53      6954041.54
      1676970.22      6954038.49      1676648.94      6954196.14
      1676457.43      6954382.48      1676299.06      6954435.75
      1676156.47      6954434.46      1676029.92      6954337.39
      1675939.16      6954437.32      1675555.00      6954438.00

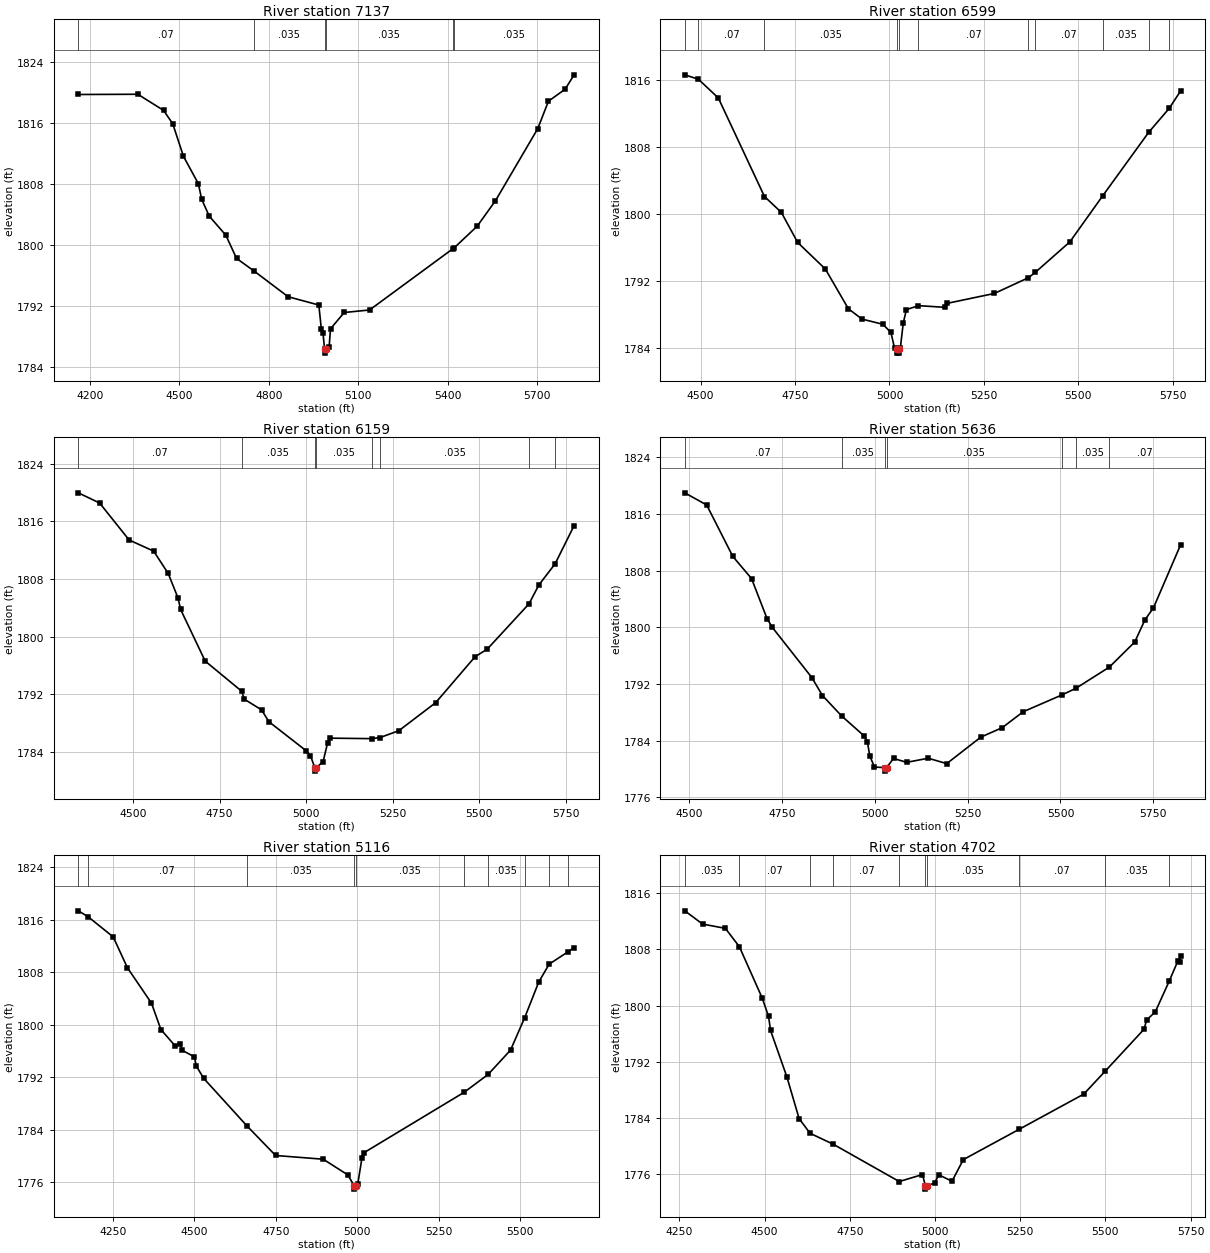
Type RM Length L Ch R = 1,7137,538,538,538
BEGIN DESCRIPTION:
Chimney Creek 1137 14.0
END DESCRIPTION:
XS GIS Cut Line= 3
      1680110.35      6950599.29      1680396.83      6951387.98
      1680679.99      6952162.97
#Sta/Elev= 30
  4160.9 1819.80  4360.6 1819.83  4446.8 1817.72  4477.7 1815.97  4513.6 1811.70
  4563.8 1808.09  4574.9 1806.06  4600.1 1803.85  4656.0 1801.34  4691.9 1798.30
  4751.1 1796.63  4864.9 1793.27  4968.1 1792.18  4976.7 1788.97  4982.0 1788.55
  4987.4 1786.37  4987.6 1785.87  4991.4 1786.37  5002.7 1786.68  5007.3 1789.06
  5053.3 1791.20  5138.4 1791.53  5416.9 1799.53  5423.2 1799.71  5499.8 1802.53
  5560.9 1805.86  5702.7 1815.30  5738.8 1818.92  5794.6 1820.49  5825.1 1822.38
#Mann=6,-1,0
  4160.9    0.07       0  4751.1   0.035       0  4987.4   0.035       0
  4991.4   0.035       0  5416.9    0.07       0  5423.2   0.035       0
Bank Sta=4987.4,4991.4
Exp/Cntr=0.3,0.1

Type RM Length L Ch R = 1,6599,440,440,440
BEGIN DESCRIPTION:
Mapping XS 26bcc22a
END DESCRIPTION:
XS GIS Cut Line= 3
      1679850.26      6951147.29      1680037.74      6951657.67
      1680412.76      6952329.58
#Sta/Elev= 30
  4458.0 1816.66  4494.1 1816.13  4546.8 1813.89  4669.0 1802.10  4713.7 1800.20
  4757.0 1796.60  4830.3 1793.42  4891.2 1788.67  4927.5 1787.43  4982.7 1786.81
  5004.0 1785.83  5013.6 1783.93  5021.1 1783.86  5021.3 1783.36  5024.8 1783.36
  5025.1 1783.86  5028.8 1783.94  5036.5 1786.93  5044.8 1788.56  5076.9 1789.04
  5147.6 1788.84  5153.3 1789.32  5277.9 1790.50  5367.9 1792.38  5386.2 1793.02
  5477.8 1796.67  5565.1 1802.20  5686.6 1809.78  5740.8 1812.64  5771.2 1814.73
#Mann=11,-1,0
  4458.0   0.035       0  4494.1    0.07       0  4669.0   0.035       0
  5021.1   0.035       0  5025.1   0.035       0  5076.9    0.07       0
  5367.9   0.035       0  5386.2    0.07       0  5565.1   0.035       0
  5686.6    0.07       0  5740.8   0.035       0
Bank Sta=5021.1,5025.1
Exp/Cntr=0.3,0.1

Type RM Length L Ch R = 1,6159,523,523,523
BEGIN DESCRIPTION:
Mapping XS 65f25b69
END DESCRIPTION:
XS GIS Cut Line= 3
      1679274.71      6951501.40      1679759.10      6951946.73
      1680337.21      6952459.74
#Sta/Elev= 30
  4342.6 1819.96  4404.1 1818.54  4489.2 1813.41  4560.1 1811.86  4602.0 1808.76
  4630.4 1805.34  4637.8 1803.76  4708.7 1796.59  4814.2 1792.40  4821.5 1791.30
  4871.4 1789.82  4892.4 1788.18  5000.6 1784.12  5012.6 1783.45  5024.8 1781.81
  5025.1 1781.31  5028.8 1781.81  5048.6 1782.57  5062.0 1785.23  5069.5 1785.89
  5189.3 1785.82  5213.3 1785.97  5267.7 1786.93  5373.9 1790.82  5487.6 1797.20
  5522.7 1798.25  5643.3 1804.55  5671.6 1807.16  5718.6 1810.11  5773.5 1815.42
#Mann=8,-1,0
  4342.6    0.07       0  4814.2   0.035       0  5024.8   0.035       0
  5028.8   0.035       0  5189.3    0.07       0  5213.3   0.035       0
  5643.3    0.07       0  5718.6   0.035       0
Bank Sta=5024.8,5028.8
Exp/Cntr=0.3,0.1

Type RM Length L Ch R = 1,5636,520,520,520
BEGIN DESCRIPTION:
Mapping XS 8f05ae9c
END DESCRIPTION:
XS GIS Cut Line= 3
      1679006.98      6951913.11      1679397.64      6952243.86
      1680053.34      6952743.45
#Sta/Elev= 30
  4487.6 1818.99  4546.6 1817.27  4616.9 1810.02  4667.5 1806.88  4709.2 1801.24
  4723.5 1799.99  4830.1 1792.90  4858.6 1790.37  4910.4 1787.48  4971.8 1784.63
  4979.5 1783.88  4986.1 1781.85  4998.8 1780.27  5027.3 1780.20  5027.5 1779.70
  5031.4 1780.20  5050.1 1781.49  5085.5 1780.94  5143.6 1781.52  5193.5 1780.76
  5285.3 1784.50  5343.2 1785.84  5399.4 1788.08  5504.1 1790.46  5541.8 1791.40
  5631.6 1794.38  5700.2 1797.93  5727.8 1801.08  5750.5 1802.74  5823.8 1811.66
#Mann=7,-1,0
  4487.6    0.07       0  4910.4   0.035       0  5027.3   0.035       0
  5031.4   0.035       0  5504.1    0.07       0  5541.8   0.035       0
  5631.6    0.07       0
Bank Sta=5027.3,5031.4
Exp/Cntr=0.3,0.1

Type RM Length L Ch R = 1,5116,414,414,414
BEGIN DESCRIPTION:
Mapping XS b4759a4c
END DESCRIPTION:
XS GIS Cut Line= 3
      1678618.97      6952259.48      1679366.39      6952676.16
      1679944.55      6953006.91
#Sta/Elev= 30
  4143.9 1817.37  4173.3 1816.49  4251.0 1813.39  4294.4 1808.70  4368.3 1803.30
  4397.3 1799.27  4440.7 1796.79  4456.7 1797.11  4462.4 1796.10  4500.1 1795.11
  4505.9 1793.71  4528.6 1791.83  4660.5 1784.62  4749.3 1780.06  4895.6 1779.49
  4971.0 1777.10  4990.7 1775.43  4990.9 1774.93  4994.8 1775.43  5001.7 1775.75
  5014.3 1779.66  5021.1 1780.50  5328.2 1789.70  5401.6 1792.42  5470.4 1796.13
  5513.9 1801.08  5557.0 1806.51  5589.0 1809.24  5646.5 1811.11  5665.7 1811.76
#Mann=10,-1,0
  4143.9   0.035       0  4173.3    0.07       0  4660.5   0.035       0
  4990.7   0.035       0  4994.8   0.035       0  5328.2    0.07       0
  5401.6   0.035       0  5513.9    0.07       0  5589.0   0.035       0
  5646.5    0.07       0
Bank Sta=4990.7,4994.8
Exp/Cntr=0.3,0.1

Type RM Length L Ch R = 1,4702,559,559,559
BEGIN DESCRIPTION:
Mapping XS 131e1ce8
END DESCRIPTION:
XS GIS Cut Line= 3
      1678426.32      6952720.44      1679105.97      6952988.66
      1679800.64      6953194.19
#Sta/Elev= 30
  4265.9 1813.50  4318.2 1811.61  4385.0 1811.00  4426.1 1808.38  4493.2 1801.05
  4511.7 1798.45  4517.6 1796.44  4565.5 1789.82  4601.4 1783.87  4633.6 1781.78
  4702.0 1780.21  4895.4 1774.90  4963.3 1775.90  4971.9 1774.32  4972.2 1773.82
  4976.1 1774.32  4998.7 1774.68  5011.5 1775.86  5050.0 1774.94  5083.3 1778.03
  5247.9 1782.37  5436.8 1787.37  5499.1 1790.61  5613.5 1796.61  5621.3 1797.93
  5646.8 1799.11  5688.3 1803.56  5713.3 1806.40  5718.6 1806.16  5721.0 1807.01
#Mann=10,-1,0
  4265.9   0.035       0  4426.1    0.07       0  4633.6   0.035       0
  4702.0    0.07       0  4895.4   0.035       0  4971.9   0.035       0
  4976.1   0.035       0  5247.9    0.07       0  5499.1   0.035       0
  5688.3    0.07       0
Bank Sta=4971.9,4976.1
Exp/Cntr=0.3,0.1

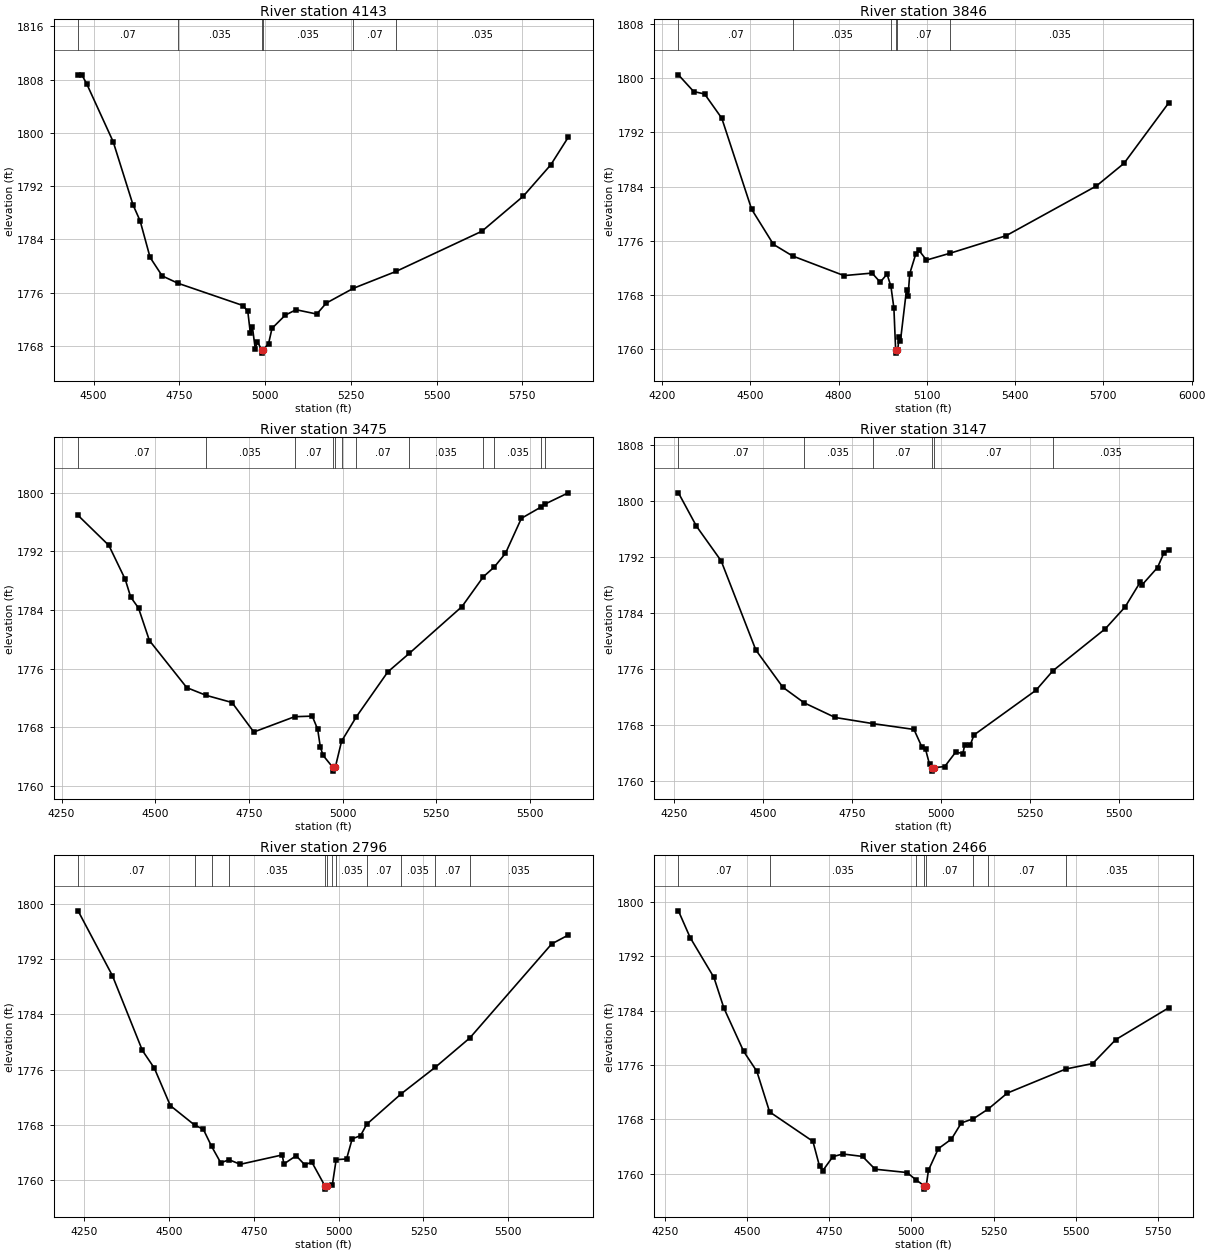
Type RM Length L Ch R = 1,4143,297,297,297
BEGIN DESCRIPTION:
Mapping XS c2000963
END DESCRIPTION:
XS GIS Cut Line= 3
      1678425.07      6952963.31      1678853.89      6953298.38
      1679735.83      6953223.73
#Sta/Elev= 30
  4454.7 1808.63  4465.7 1808.73  4480.0 1807.37  4557.1 1798.68  4614.9 1789.20
  4635.7 1786.78  4664.7 1781.30  4700.0 1778.52  4746.3 1777.41  4936.0 1774.06
  4949.6 1773.18  4956.8 1770.00  4963.1 1770.78  4971.3 1767.57  4977.6 1768.62
  4990.0 1767.42  4990.2 1766.92  4994.2 1767.42  5010.1 1768.34  5020.1 1770.64
  5058.9 1772.63  5090.3 1773.44  5150.6 1772.79  5178.4 1774.44  5257.4 1776.66
  5381.5 1779.19  5632.3 1785.24  5752.7 1790.50  5833.0 1795.22  5884.0 1799.37
#Mann=6,-1,0
  4454.7    0.07       0  4746.3   0.035       0  4990.0   0.035       0
  4994.2   0.035       0  5257.4    0.07       0  5381.5   0.035       0
Bank Sta=4990,4994.2
Exp/Cntr=0.3,0.1

Type RM Length L Ch R = 1,3846,371,371,371
BEGIN DESCRIPTION:
Mapping XS 3e0d6f2b
END DESCRIPTION:
XS GIS Cut Line= 3
      1678214.98      6953216.77      1678853.89      6953595.25
      1679727.18      6953294.90
#Sta/Elev= 30
  4255.8 1800.51  4307.7 1798.04  4344.8 1797.68  4403.2 1794.10  4504.6 1780.66
  4578.7 1775.47  4643.7 1773.76  4818.5 1770.86  4914.0 1771.23  4941.6 1769.89
  4964.8 1771.08  4978.0 1769.27  4988.1 1766.06  4994.0 1759.91  4994.3 1759.41
  4998.3 1759.91  5001.6 1759.91  5005.1 1761.79  5010.4 1761.23  5031.0 1768.80
  5036.3 1767.81  5041.9 1771.15  5062.3 1774.03  5073.6 1774.57  5098.8 1773.15
  5180.4 1774.18  5369.4 1776.75  5676.4 1784.10  5770.1 1787.44  5921.9 1796.36
#Mann=6,-1,0
  4255.8    0.07       0  4643.7   0.035       0  4978.0    0.07       0
  4994.0    0.07       0  4998.3    0.07       0  5180.4   0.035       0
Bank Sta=4994,4998.3
Exp/Cntr=0.3,0.1

Type RM Length L Ch R = 1,3475,328,328,328
BEGIN DESCRIPTION:
Mapping XS 5a3403d6
END DESCRIPTION:
XS GIS Cut Line= 3
      1678174.07      6953272.38      1678601.57      6953836.60
      1678916.25      6954348.76
#Sta/Elev= 30
  4293.9 1796.92  4376.2 1792.82  4419.9 1788.18  4434.4 1785.77  4455.3 1784.27
  4484.4 1779.83  4584.2 1773.40  4635.8 1772.35  4704.9 1771.37  4763.1 1767.34
  4872.0 1769.43  4919.2 1769.51  4933.7 1767.71  4940.8 1765.27  4948.3 1764.14
  4974.3 1762.50  4974.8 1762.00  4980.6 1762.50  4997.5 1766.09  5037.2 1769.44
  5120.8 1775.54  5178.7 1778.10  5319.0 1784.47  5376.0 1788.54  5405.0 1789.86
  5435.0 1791.73  5477.6 1796.52  5530.0 1798.06  5540.8 1798.47  5602.9 1800.00
#Mann=12,-1,0
  4293.9    0.07       0  4635.8   0.035       0  4872.0    0.07       0
  4974.3   0.035       0  4980.6    0.07       0  4997.5   0.035       0
  5037.2    0.07       0  5178.7   0.035       0  5376.0    0.07       0
  5405.0   0.035       0  5530.0    0.07       0  5540.8   0.035       0
Bank Sta=4974.3,4980.6
Exp/Cntr=0.3,0.1

Type RM Length L Ch R = 1,3147,351,351,351
BEGIN DESCRIPTION:
Mapping XS c05047d1
END DESCRIPTION:
XS GIS Cut Line= 3
      1678019.99      6953257.22      1678306.43      6953942.94
      1678447.49      6954561.41
#Sta/Elev= 30
  4262.2 1801.16  4313.0 1796.38  4382.3 1791.43  4479.8 1778.68  4555.7 1773.36
  4615.4 1771.14  4702.6 1769.04  4807.8 1768.17  4924.1 1767.33  4945.8 1764.87
  4956.6 1764.49  4967.8 1762.33  4975.1 1761.87  4975.6 1761.37  4981.5 1761.87
  5010.5 1762.03  5041.3 1764.09  5061.5 1763.89  5066.6 1765.13  5082.3 1765.12
  5092.6 1766.54  5267.0 1772.94  5314.2 1775.71  5461.8 1781.73  5517.2 1784.84
  5560.2 1788.43  5565.3 1788.02  5608.3 1790.48  5625.9 1792.52  5639.7 1793.05
#Mann=6,-1,0
  4262.2    0.07       0  4615.4   0.035       0  4807.8    0.07       0
  4975.1    0.07       0  4981.5    0.07       0  5314.2   0.035       0
Bank Sta=4975.1,4981.5
Exp/Cntr=0.3,0.1

Type RM Length L Ch R = 1,2796,330,330,330
BEGIN DESCRIPTION:
Mapping XS 9f79bb8f
END DESCRIPTION:
XS GIS Cut Line= 3
      1677813.80      6953339.60      1678000.44      6954086.17
      1678160.96      6954743.41
#Sta/Elev= 30
  4231.3 1798.98  4332.7 1789.60  4421.1 1778.79  4456.4 1776.23  4503.5 1770.82
  4575.1 1768.01  4600.7 1767.41  4625.0 1764.95  4652.3 1762.55  4676.6 1763.00
  4709.7 1762.34  4833.4 1763.69  4838.5 1762.39  4874.6 1763.58  4899.7 1762.28
  4921.0 1762.64  4959.0 1759.25  4959.5 1758.75  4965.5 1759.25  4981.3 1759.35
  4992.6 1763.01  5023.3 1763.11  5039.9 1766.02  5064.5 1766.48  5082.8 1768.13
  5184.2 1772.52  5285.6 1776.39  5387.0 1780.61  5628.4 1794.20  5677.4 1795.48
#Mann=12,-1,0
  4231.3    0.07       0  4575.1   0.035       0  4625.0    0.07       0
  4676.6   0.035       0  4959.0   0.035       0  4965.5   0.035       0
  4981.3    0.07       0  4992.6   0.035       0  5082.8    0.07       0
  5184.2   0.035       0  5285.6    0.07       0  5387.0   0.035       0
Bank Sta=4959,4965.5
Exp/Cntr=0.3,0.1

Type RM Length L Ch R = 1,2466,475,475,475
BEGIN DESCRIPTION:
Mapping XS 2401b7fc
END DESCRIPTION:
XS GIS Cut Line= 3
      1677625.88      6953390.41      1677701.83      6954100.06
      1677732.22      6954879.17
#Sta/Elev= 30
  4290.2 1798.68  4326.0 1794.74  4398.4 1788.88  4428.6 1784.39  4488.9 1778.01
  4529.1 1775.07  4568.0 1769.10  4699.9 1764.77  4720.2 1761.08  4730.3 1760.48
  4760.5 1762.51  4790.6 1762.91  4851.0 1762.55  4889.4 1760.67  4986.7 1760.18
  5012.7 1759.15  5038.6 1758.24  5039.1 1757.74  5045.1 1758.24  5051.9 1760.53
  5081.9 1763.69  5121.9 1765.10  5152.0 1767.48  5188.9 1768.10  5234.3 1769.54
  5292.1 1771.87  5470.3 1775.41  5552.3 1776.22  5622.3 1779.73  5783.6 1784.41
#Mann=8,-1,0
  4290.2    0.07       0  4568.0   0.035       0  5012.7    0.07       0
  5038.6   0.035       0  5045.1    0.07       0  5188.9   0.035       0
  5234.3    0.07       0  5470.3   0.035       0
Bank Sta=5038.6,5045.1
Exp/Cntr=0.3,0.1

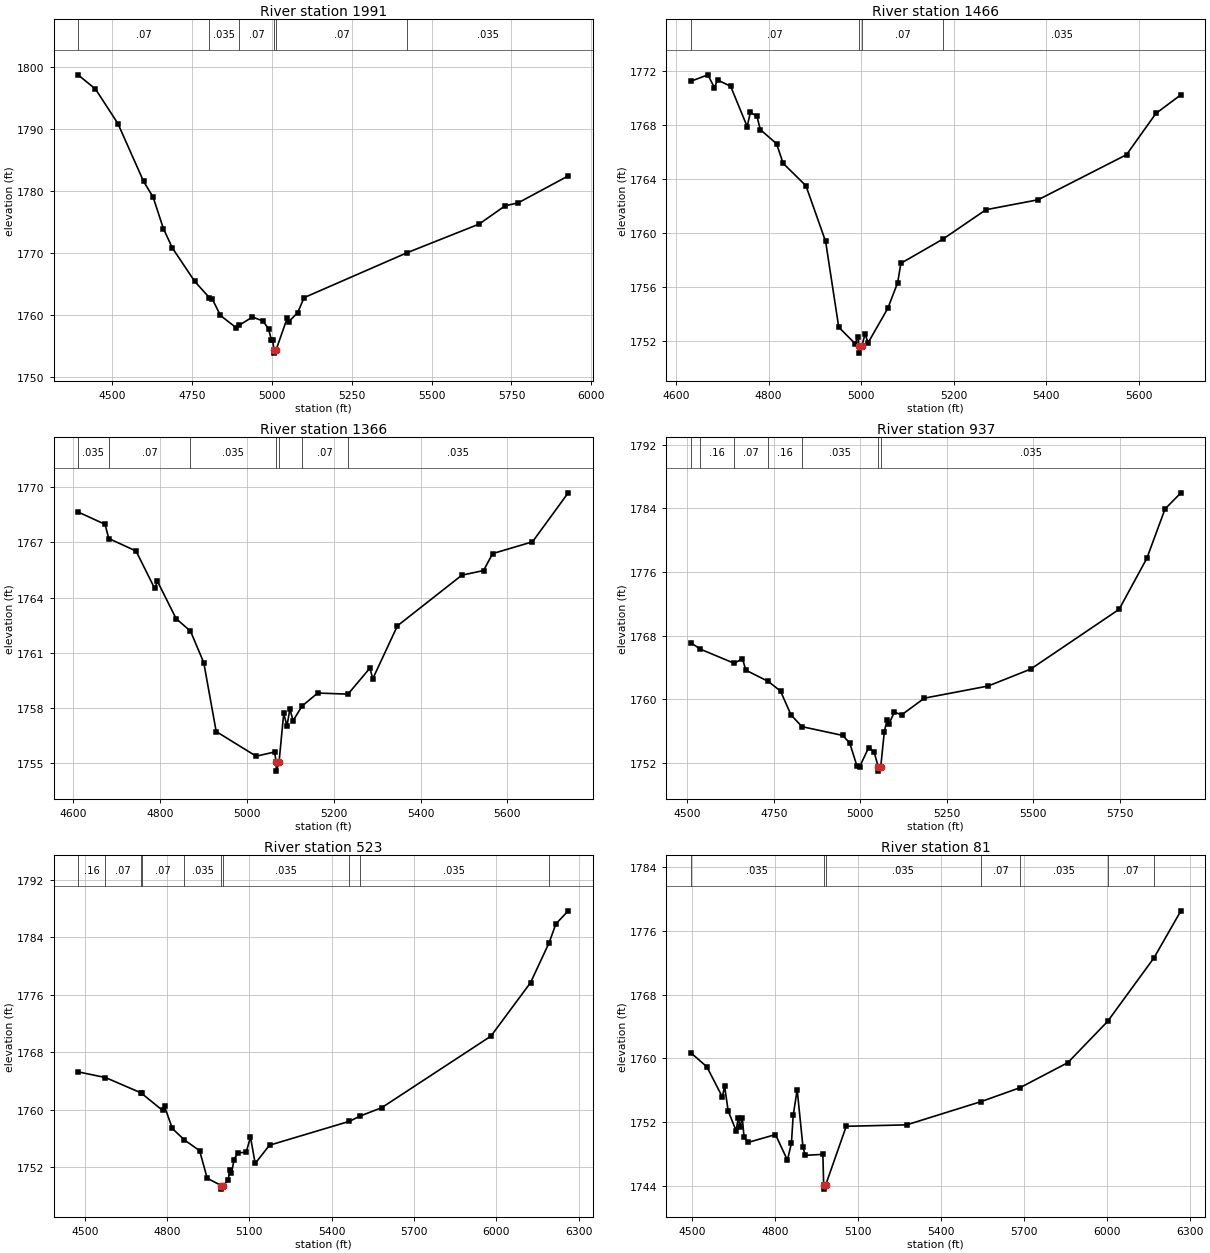
Type RM Length L Ch R = 1,1991,525,525,525
BEGIN DESCRIPTION:
Mapping XS 1bbe5b8e
END DESCRIPTION:
XS GIS Cut Line= 3
      1677233.08      6953533.64      1677272.15      6954141.29
      1677424.05      6955052.72
#Sta/Elev= 30
  4394.5 1798.80  4449.0 1796.50  4519.1 1790.93  4599.3 1781.59  4629.3 1779.03
  4661.3 1773.96  4689.5 1770.81  4759.6 1765.40  4805.3 1762.78  4814.4 1762.55
  4839.8 1759.91  4889.9 1757.89  4898.1 1758.31  4940.0 1759.66  4972.5 1759.01
  4990.1 1757.77  4999.2 1755.94  5003.4 1755.94  5006.9 1754.32  5007.4 1753.82
  5013.6 1754.32  5048.4 1759.45  5053.5 1758.91  5081.2 1760.35  5101.4 1762.79
  5423.2 1770.04  5648.9 1774.68  5730.0 1777.63  5770.5 1778.10  5927.4 1782.46
#Mann=6,-1,0
  4394.5    0.07       0  4805.3   0.035       0  4898.1    0.07       0
  5006.9    0.07       0  5013.6    0.07       0  5423.2   0.035       0
Bank Sta=5006.9,5013.6
Exp/Cntr=0.3,0.1

Type RM Length L Ch R = 1,1466,100,100,100
BEGIN DESCRIPTION:
Mapping XS 87015204
END DESCRIPTION:
XS GIS Cut Line= 3
      1676565.15      6953855.59      1676814.68      6954128.99
      1677300.37      6954619.02
#Sta/Elev= 30
  4631.6 1771.27  4668.6 1771.75  4682.8 1770.80  4689.5 1771.37  4717.9 1770.90
  4753.7 1767.91  4760.5 1768.97  4774.7 1768.68  4782.1 1767.69  4817.2 1766.64
  4831.4 1765.19  4880.7 1763.53  4923.3 1759.40  4951.7 1753.04  4986.9 1751.83
  4994.2 1752.35  4994.9 1751.62  4995.4 1751.12  5001.6 1751.62  5008.4 1752.53
  5015.4 1751.90  5057.8 1754.44  5079.1 1756.34  5086.1 1757.78  5177.4 1759.58
  5270.0 1761.75  5383.1 1762.49  5574.1 1765.83  5637.7 1768.89  5691.7 1770.27
#Mann=4,-1,0
  4631.6    0.07       0  4994.9    0.07       0  5001.6    0.07       0
  5177.4   0.035       0
Bank Sta=4994.9,5001.6
Exp/Cntr=0.3,0.1

Type RM Length L Ch R = 1,1366,429,429,429
BEGIN DESCRIPTION:
Mapping XS 57851d56
END DESCRIPTION:
XS GIS Cut Line= 3
      1676473.94      6953870.71      1676725.70      6954168.05
      1677265.66      6954673.32
#Sta/Elev= 30
  4611.1 1768.65  4673.3 1767.98  4681.8 1767.21  4744.7 1766.53  4787.6 1764.50
  4794.1 1764.88  4837.0 1762.86  4870.1 1762.18  4900.7 1760.47  4929.3 1756.73
  5021.4 1755.39  5063.9 1755.62  5067.4 1755.08  5067.9 1754.58  5074.1 1755.08
  5084.9 1757.72  5092.3 1757.03  5099.1 1757.95  5106.4 1757.32  5127.0 1758.11
  5163.1 1758.82  5232.9 1758.76  5283.3 1760.17  5290.1 1759.60  5346.8 1762.47
  5495.3 1765.22  5545.1 1765.47  5566.1 1766.39  5657.9 1767.03  5740.2 1769.69
#Mann=7,-1,0
  4611.1   0.035       0  4681.8    0.07       0  4870.1   0.035       0
  5067.4   0.035       0  5074.1   0.035       0  5127.0    0.07       0
  5232.9   0.035       0
Bank Sta=5067.4,5074.1
Exp/Cntr=0.3,0.1

Type RM Length L Ch R = 1,937,414,414,414
BEGIN DESCRIPTION:
Mapping XS 4d6954c7
END DESCRIPTION:
XS GIS Cut Line= 3
      1676413.20      6953898.97      1676380.65      6954389.41
      1676850.80      6955186.70
#Sta/Elev= 30
  4509.9 1767.10  4537.8 1766.28  4635.7 1764.50  4659.3 1765.09  4669.3 1763.63
  4733.6 1762.23  4769.5 1761.00  4799.6 1758.01  4831.5 1756.52  4949.9 1755.41
  4969.9 1754.41  4990.0 1751.62  4998.2 1751.48  5024.3 1753.88  5040.0 1753.33
  5052.2 1751.42  5052.7 1750.92  5059.1 1751.42  5069.4 1755.83  5077.1 1757.32
  5082.9 1756.89  5098.5 1758.34  5120.0 1758.02  5185.5 1760.11  5369.8 1761.64
  5492.7 1763.77  5748.4 1771.30  5828.4 1777.71  5881.2 1783.94  5927.0 1785.97
#Mann=7,-1,0
  4509.9   0.035       0  4537.8    0.16       0  4635.7    0.07       0
  4733.6    0.16       0  4831.5   0.035       0  5052.2   0.035       0
  5059.1   0.035       0
Bank Sta=5052.2,5059.1
Exp/Cntr=0.3,0.1

Type RM Length L Ch R = 1,523,442,442,442
BEGIN DESCRIPTION:
Mapping XS 687a04e3
END DESCRIPTION:
XS GIS Cut Line= 4
      1676367.63      6953946.67      1676367.63      6953948.87
      1676018.24      6954339.49      1676536.90      6955487.48
#Sta/Elev= 30
  4475.8 1765.28  4575.8 1764.49  4704.0 1762.38  4707.4 1762.29  4784.1 1759.91
  4790.8 1760.50  4819.2 1757.41  4862.7 1755.83  4918.7 1754.32  4946.4 1750.49
  4997.3 1749.47  4997.8 1748.97  5004.2 1749.47  5022.4 1750.19  5029.3 1751.64
  5034.8 1751.18  5044.3 1753.09  5057.9 1754.02  5088.2 1754.09  5104.1 1756.21
  5121.2 1752.54  5173.5 1755.08  5464.6 1758.40  5501.8 1759.11  5582.0 1760.29
  5980.2 1770.25  6124.4 1777.68  6192.2 1783.24  6216.9 1785.86  6261.8 1787.68
#Mann=10,-1,0
  4475.8    0.16       0  4575.8    0.07       0  4704.0    0.16       0
  4707.4    0.07       0  4862.7   0.035       0  4997.3   0.035       0
  5004.2   0.035       0  5464.6    0.07       0  5501.8   0.035       0
  6192.2    0.07       0
Bank Sta=4997.3,5004.2
Exp/Cntr=0.3,0.1

Type RM Length L Ch R = 1,81,0,0,0
BEGIN DESCRIPTION:
Chimney Creek 1137 1.0
END DESCRIPTION:
XS GIS Cut Line= 3
      1676030.72      6954122.81      1675636.30      6954438.01
      1676199.92      6955573.08
#Sta/Elev= 30
  4495.1 1760.71  4553.4 1758.94  4609.4 1755.14  4617.4 1756.52  4630.4 1753.40
  4659.0 1750.91  4667.0 1752.48  4673.4 1751.40  4681.4 1752.54  4687.8 1750.12
  4702.2 1749.43  4801.5 1750.42  4844.7 1747.20  4859.1 1749.34  4865.5 1752.82
  4879.9 1756.06  4900.8 1748.88  4908.8 1747.81  4972.8 1747.93  4975.7 1744.06
  4976.2 1743.56  4982.7 1744.06  5057.3 1751.46  5275.8 1751.64  5545.4 1754.57
  5685.4 1756.31  5858.4 1759.46  6002.1 1764.64  6170.0 1772.64  6267.3 1778.55
#Mann=7,-1,0
  4495.1   0.035       0  4975.7   0.035       0  4982.7   0.035       0
  5545.4    0.07       0  5685.4   0.035       0  6002.1    0.07       0
  6170.0   0.035       0
Bank Sta=4975.7,4982.7
Exp/Cntr=0.3,0.1

Chan Stop Cuts=-1