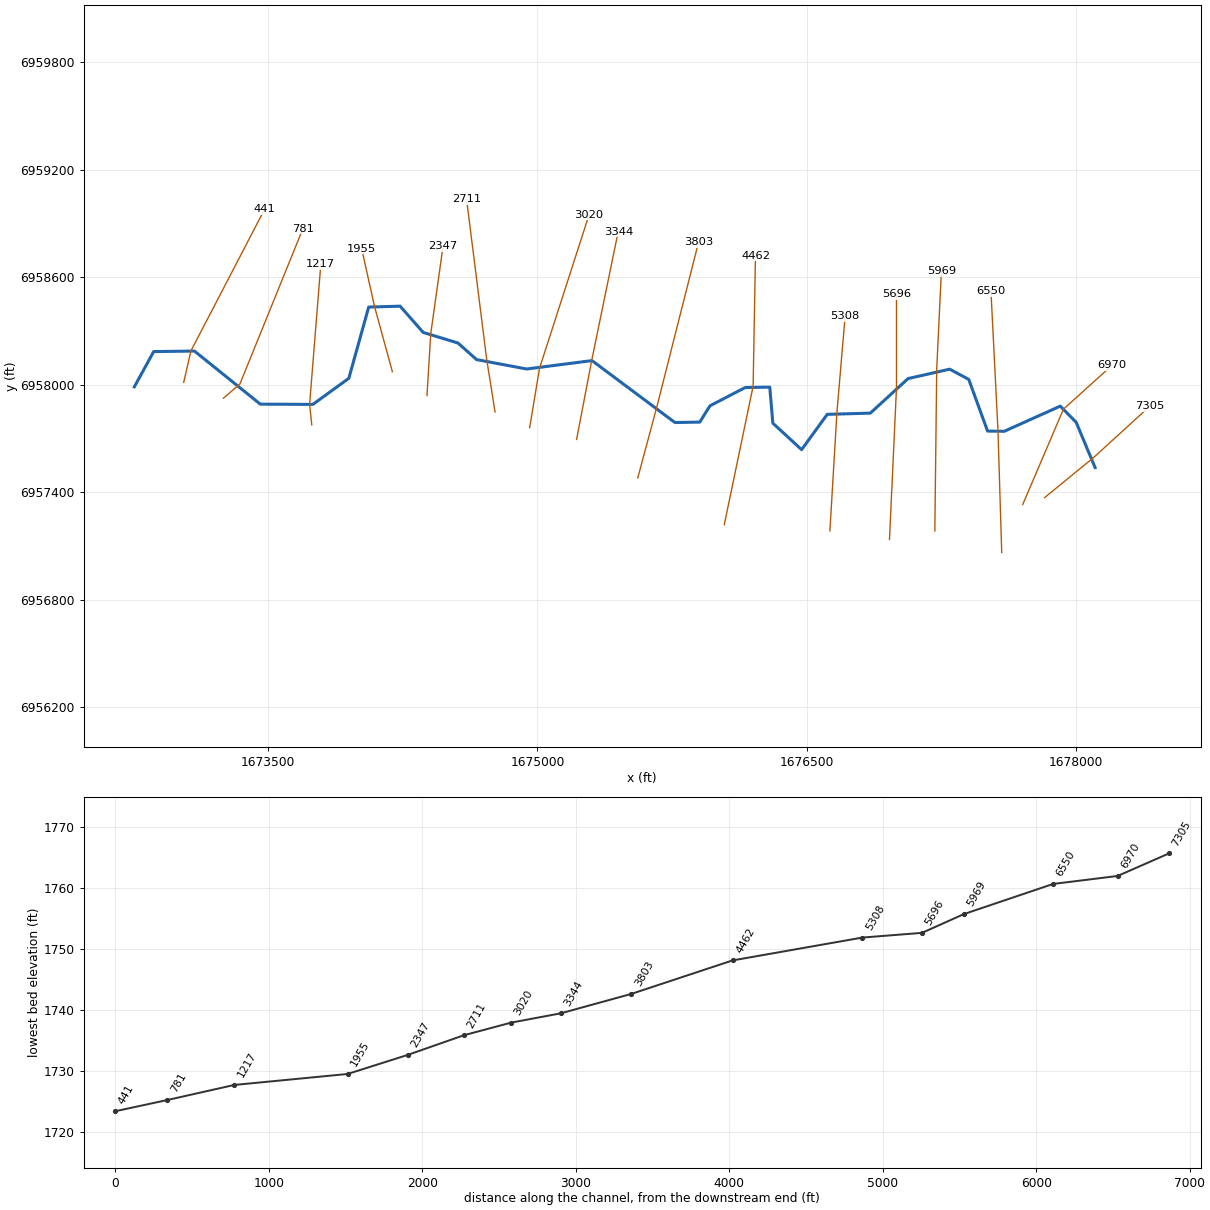
--- Chimney Creek 1140.prj (project) ---

Proj Title=Chimney Creek 1140 Base Level Engineering
Current Plan=p01
Default Exp/Contr=0.3,0.1
English Units
Geom File=g01
Flow File=f01
Plan File=p01
BEGIN DESCRIPTION:
Chimney Creek 1140
END DESCRIPTION:

--- Chimney Creek 1140.p01 (plan) ---

Plan Title=Multiple Run
Short Identifier=Multiple
Geom File=g01
Flow File=f01
Subcritical Flow
K Sum by GR= 0
Std Step Tol= 0.01
Critical Tol= 0.01
Num of Std Step Trials= 20
Max Error Tol= 0.3
Flow Tol Ratio= 0.001
Split Flow NTrial= 30
Split Flow Tol= 0.02
Split Flow Ratio= 0.02
Log Output Level= 0
Friction Slope Method= 1
Unsteady Friction Slope Method= 2
Unsteady Bridges Friction Slope Method= 1
Parabolic Critical Depth
Global Vel Dist=  1 , 1 , 1
Global Log Level= 0
CheckData=True
Encroach Param= -1, 0, 0, 0
BEGIN DESCRIPTION:
Multiple Run
END DESCRIPTION:

--- Chimney Creek 1140.f01 (steady flow) ---

Flow Title=Multiple
Number of Profiles=7
Profile Names=10-year,25-year,50-year,1pct_min,100-year,1pct_plu,500-year
River Rch & RM= Chimney Creek 11,Reach-1,7305
     256     354     435     267     532    1062     805
River Rch & RM= Chimney Creek 11,Reach-1,5969
     384     541     673     416     831    1658    1284
Boundary for River Rch & Prof#=Chimney Creek 11,Reach-1,1
Up Type=0
Dn Type=3
Dn Slope=0.005
Boundary for River Rch & Prof#=Chimney Creek 11,Reach-1,2
Up Type=0
Dn Type=3
Dn Slope=0.005
Boundary for River Rch & Prof#=Chimney Creek 11,Reach-1,3
Up Type=0
Dn Type=3
Dn Slope=0.005
Boundary for River Rch & Prof#=Chimney Creek 11,Reach-1,4
Up Type=0
Dn Type=3
Dn Slope=0.005
Boundary for River Rch & Prof#=Chimney Creek 11,Reach-1,5
Up Type=0
Dn Type=3
Dn Slope=0.005
Boundary for River Rch & Prof#=Chimney Creek 11,Reach-1,6
Up Type=0
Dn Type=3
Dn Slope=0.005
Boundary for River Rch & Prof#=Chimney Creek 11,Reach-1,7
Up Type=0
Dn Type=3
Dn Slope=0.005

--- Chimney Creek 1140.g01 (geometry) ---

Geom Title=Existing Conditions

River Reach=Chimney Creek 11,Reach-1
Reach XY= 30
      1678105.00      6957538.00      1677999.48      6957790.44
      1677911.07      6957880.53      1677599.03      6957740.14
      1677506.25      6957741.36      1677401.50      6958029.54
      1677295.36      6958086.66      1677063.62      6958034.16
      1676853.54      6957841.54      1676613.38      6957834.62
      1676470.71      6957637.74      1676310.46      6957785.55
      1676293.51      6957986.53      1676156.56      6957984.26
      1675960.62      6957882.37      1675903.73      6957791.47
      1675765.44      6957789.04      1675303.53      6958134.46
      1674939.83      6958087.57      1674660.86      6958140.07
      1674557.42      6958232.46      1674363.48      6958291.51
      1674235.02      6958438.05      1674060.08      6958432.97
      1673949.48      6958035.56      1673749.07      6957890.24
      1673456.46      6957891.54      1673089.84      6958187.61
      1672862.99      6958184.78      1672755.00      6957988.00

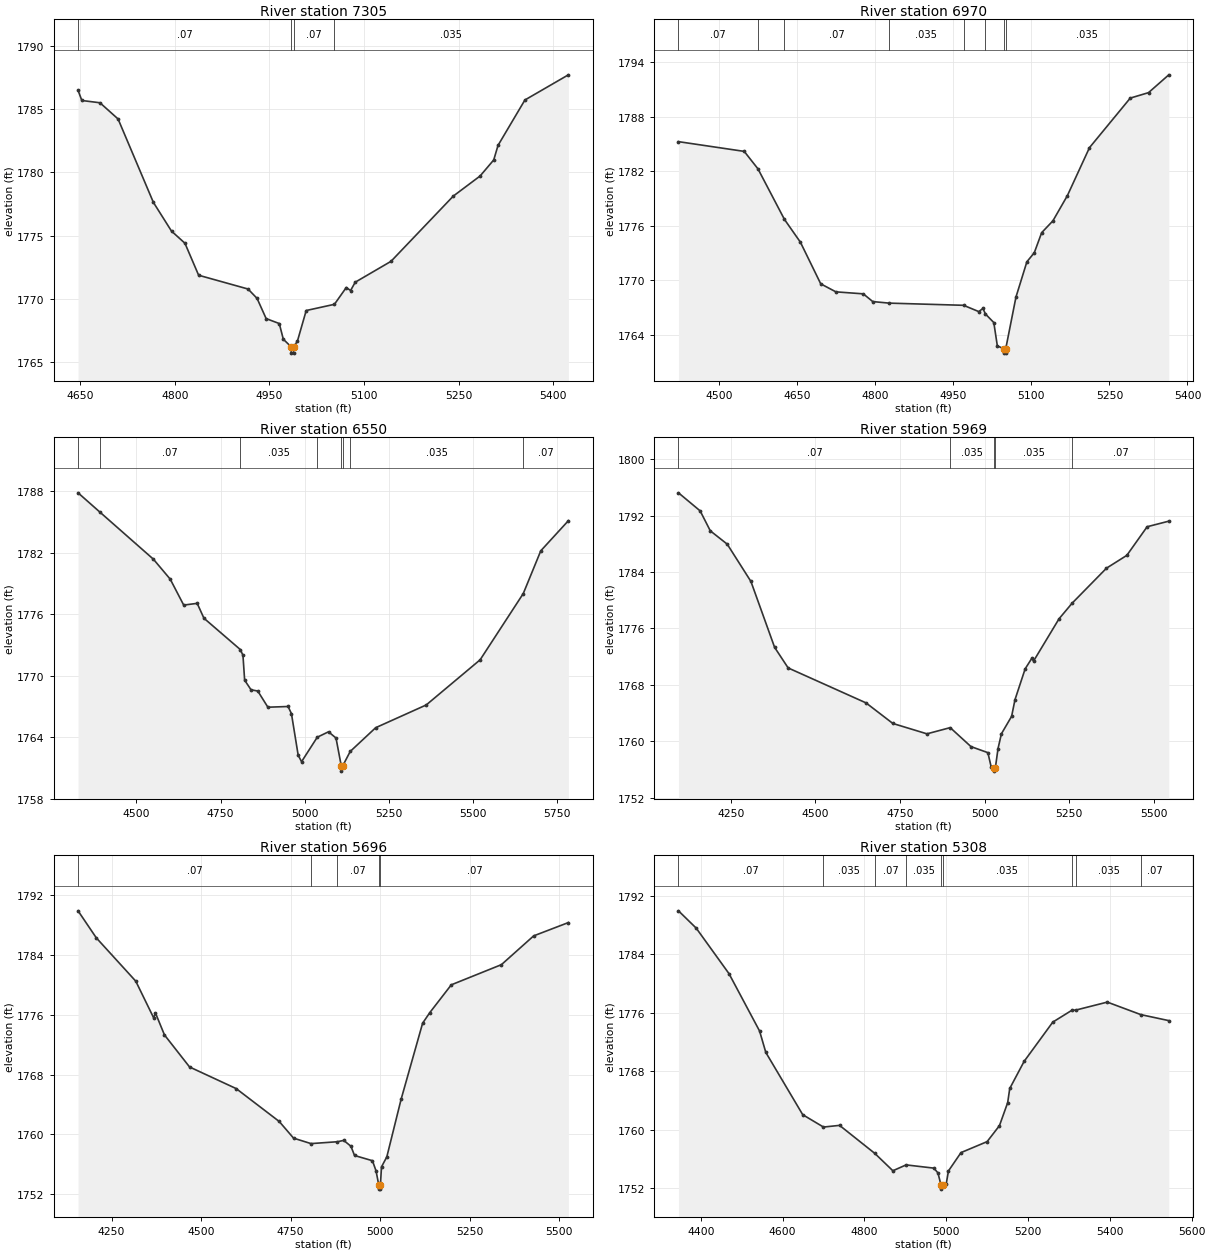
Type RM Length L Ch R = 1,7305,335,335,335
BEGIN DESCRIPTION:
Chimney Creek 1140 12.0
END DESCRIPTION:
XS GIS Cut Line= 3
      1677823.99      6957370.38      1678097.21      6957594.20
      1678409.94      6957880.37
#Sta/Elev= 30
  4646.8 1786.49  4652.8 1785.69  4681.5 1785.51  4710.2 1784.23  4766.2 1777.63
  4794.9 1775.36  4816.2 1774.40  4837.9 1771.87  4916.2 1770.78  4930.5 1770.04
  4944.9 1768.44  4965.7 1768.05  4972.1 1766.81  4984.5 1766.21  4984.8 1765.71
  4988.3 1765.71  4988.5 1766.21  4994.4 1766.65  5008.4 1769.08  5053.1 1769.57
  5071.9 1770.90  5078.7 1770.66  5086.1 1771.32  5142.8 1772.97  5241.5 1778.13
  5284.0 1779.72  5305.6 1780.99  5312.4 1782.14  5355.0 1785.73  5423.9 1787.72
#Mann=4,-1,0
  4646.8    0.07       0  4984.5    0.07       0  4988.5    0.07       0
  5053.1   0.035       0
Bank Sta=4984.5,4988.5
Exp/Cntr=0.3,0.1

Type RM Length L Ch R = 1,6970,420,420,420
BEGIN DESCRIPTION:
Mapping XS cda2f840
END DESCRIPTION:
XS GIS Cut Line= 3
      1677702.25      6957332.42      1677928.80      6957863.64
      1678199.64      6958108.45
#Sta/Elev= 30
  4421.5 1785.27  4547.9 1784.20  4574.3 1782.28  4625.1 1776.73  4655.9 1774.21
  4695.0 1769.63  4724.1 1768.75  4776.8 1768.53  4795.0 1767.68  4826.4 1767.51
  4969.6 1767.27  4998.7 1766.58  5006.8 1766.92  5011.7 1766.31  5027.7 1765.37
  5034.5 1762.80  5046.7 1762.51  5046.9 1762.01  5050.4 1762.01  5050.7 1762.51
  5070.3 1768.18  5091.3 1772.06  5105.5 1773.05  5119.7 1775.26  5141.3 1776.56
  5169.1 1779.33  5211.6 1784.61  5290.0 1790.06  5325.1 1790.66  5364.1 1792.62
#Mann=8,-1,0
  4421.5    0.07       0  4574.3   0.035       0  4625.1    0.07       0
  4826.4   0.035       0  4969.6    0.07       0  5011.7   0.035       0
  5046.7    0.07       0  5050.7   0.035       0
Bank Sta=5046.7,5050.7
Exp/Cntr=0.3,0.1

Type RM Length L Ch R = 1,6550,581,581,581
BEGIN DESCRIPTION:
Mapping XS 2aceb8f9
END DESCRIPTION:
XS GIS Cut Line= 3
      1677585.04      6957064.21      1677564.21      6957743.85
      1677525.15      6958519.90
#Sta/Elev= 30
  4326.7 1787.87  4391.2 1786.00  4550.6 1781.39  4600.6 1779.44  4640.6 1776.91
  4680.7 1777.08  4700.7 1775.63  4808.8 1772.57  4816.7 1772.01  4821.7 1769.58
  4840.7 1768.64  4860.7 1768.52  4890.8 1766.94  4950.8 1767.01  4960.8 1766.31
  4980.8 1762.25  4990.8 1761.62  5037.5 1764.01  5070.9 1764.54  5093.2 1763.93
  5108.9 1761.20  5109.2 1760.70  5112.9 1761.20  5135.4 1762.62  5211.1 1764.94
  5361.3 1767.16  5521.5 1771.57  5649.7 1778.04  5701.7 1782.21  5783.7 1785.15
#Mann=8,-1,0
  4326.7   0.035       0  4391.2    0.07       0  4808.8   0.035       0
  5037.5    0.07       0  5108.9   0.035       0  5112.9    0.07       0
  5135.4   0.035       0  5649.7    0.07       0
Bank Sta=5108.9,5112.9
Exp/Cntr=0.3,0.1

Type RM Length L Ch R = 1,5969,273,273,273
BEGIN DESCRIPTION:
Mapping XS ca4b1540
END DESCRIPTION:
XS GIS Cut Line= 3
      1677212.65      6957183.99      1677223.07      6958087.60
      1677249.11      6958631.90
#Sta/Elev= 30
  4095.5 1795.24  4159.5 1792.68  4189.5 1789.85  4239.5 1787.96  4309.5 1782.67
  4379.5 1773.32  4419.5 1770.40  4649.6 1765.44  4728.9 1762.52  4829.6 1761.05
  4898.3 1761.93  4959.6 1759.24  5009.6 1758.38  5019.6 1756.30  5027.5 1756.26
  5027.8 1755.76  5031.8 1756.26  5039.6 1758.97  5049.6 1761.06  5079.7 1763.53
  5089.7 1765.90  5119.7 1770.27  5139.5 1771.77  5144.5 1771.37  5219.8 1777.37
  5258.8 1779.60  5360.0 1784.55  5420.1 1786.37  5480.1 1790.43  5544.1 1791.22
#Mann=5,-1,0
  4095.5    0.07       0  4898.3   0.035       0  5027.5   0.035       0
  5031.8   0.035       0  5258.8    0.07       0
Bank Sta=5027.5,5031.8
Exp/Cntr=0.3,0.1

Type RM Length L Ch R = 1,5696,388,388,388
BEGIN DESCRIPTION:
Mapping XS fdd9b44c
END DESCRIPTION:
XS GIS Cut Line= 3
      1676960.04      6957137.05      1676999.11      6957983.43
      1676999.11      6958504.95
#Sta/Elev= 30
  4156.6 1789.91  4207.6 1786.29  4317.7 1780.50  4367.7 1775.59  4372.7 1776.24
  4397.8 1773.31  4467.9 1769.02  4598.0 1766.13  4718.2 1761.73  4758.2 1759.50
  4806.9 1758.77  4880.5 1759.02  4898.3 1759.20  4918.4 1758.41  4928.4 1757.18
  4978.4 1756.48  4988.4 1755.13  4996.3 1753.18  4996.6 1752.68  5000.3 1752.68
  5000.6 1753.18  5003.7 1755.66  5018.5 1756.99  5058.5 1764.71  5118.5 1774.88
  5138.5 1776.29  5198.5 1780.01  5338.5 1782.71  5428.5 1786.56  5525.4 1788.34
#Mann=5,-1,0
  4156.6    0.07       0  4806.9   0.035       0  4880.5    0.07       0
  4996.3    0.07       0  5000.6    0.07       0
Bank Sta=4996.3,5000.6
Exp/Cntr=0.3,0.1

Type RM Length L Ch R = 1,5308,846,846,846
BEGIN DESCRIPTION:
Mapping XS 9750433e
END DESCRIPTION:
XS GIS Cut Line= 3
      1676628.30      6957184.75      1676667.37      6957844.51
      1676712.94      6958380.57
#Sta/Elev= 30
  4345.2 1789.93  4388.5 1787.57  4468.7 1781.35  4543.5 1773.51  4558.8 1770.58
  4649.0 1762.08  4699.7 1760.39  4739.1 1760.62  4825.3 1756.79  4869.4 1754.42
  4901.8 1755.22  4969.5 1754.78  4979.6 1754.13  4987.4 1752.41  4987.7 1751.91
  4991.7 1752.41  4999.6 1752.55  5005.4 1754.40  5036.0 1756.90  5099.9 1758.40
  5130.0 1760.58  5150.1 1763.72  5155.2 1765.66  5190.3 1769.36  5260.5 1774.73
  5306.7 1776.33  5317.5 1776.38  5393.7 1777.46  5475.7 1775.75  5544.1 1774.93
#Mann=9,-1,0
  4345.2    0.07       0  4699.7   0.035       0  4825.3    0.07       0
  4901.8   0.035       0  4987.4   0.035       0  4991.7   0.035       0
  5306.7    0.07       0  5317.5   0.035       0  5475.7    0.07       0
Bank Sta=4987.4,4991.7
Exp/Cntr=0.3,0.1

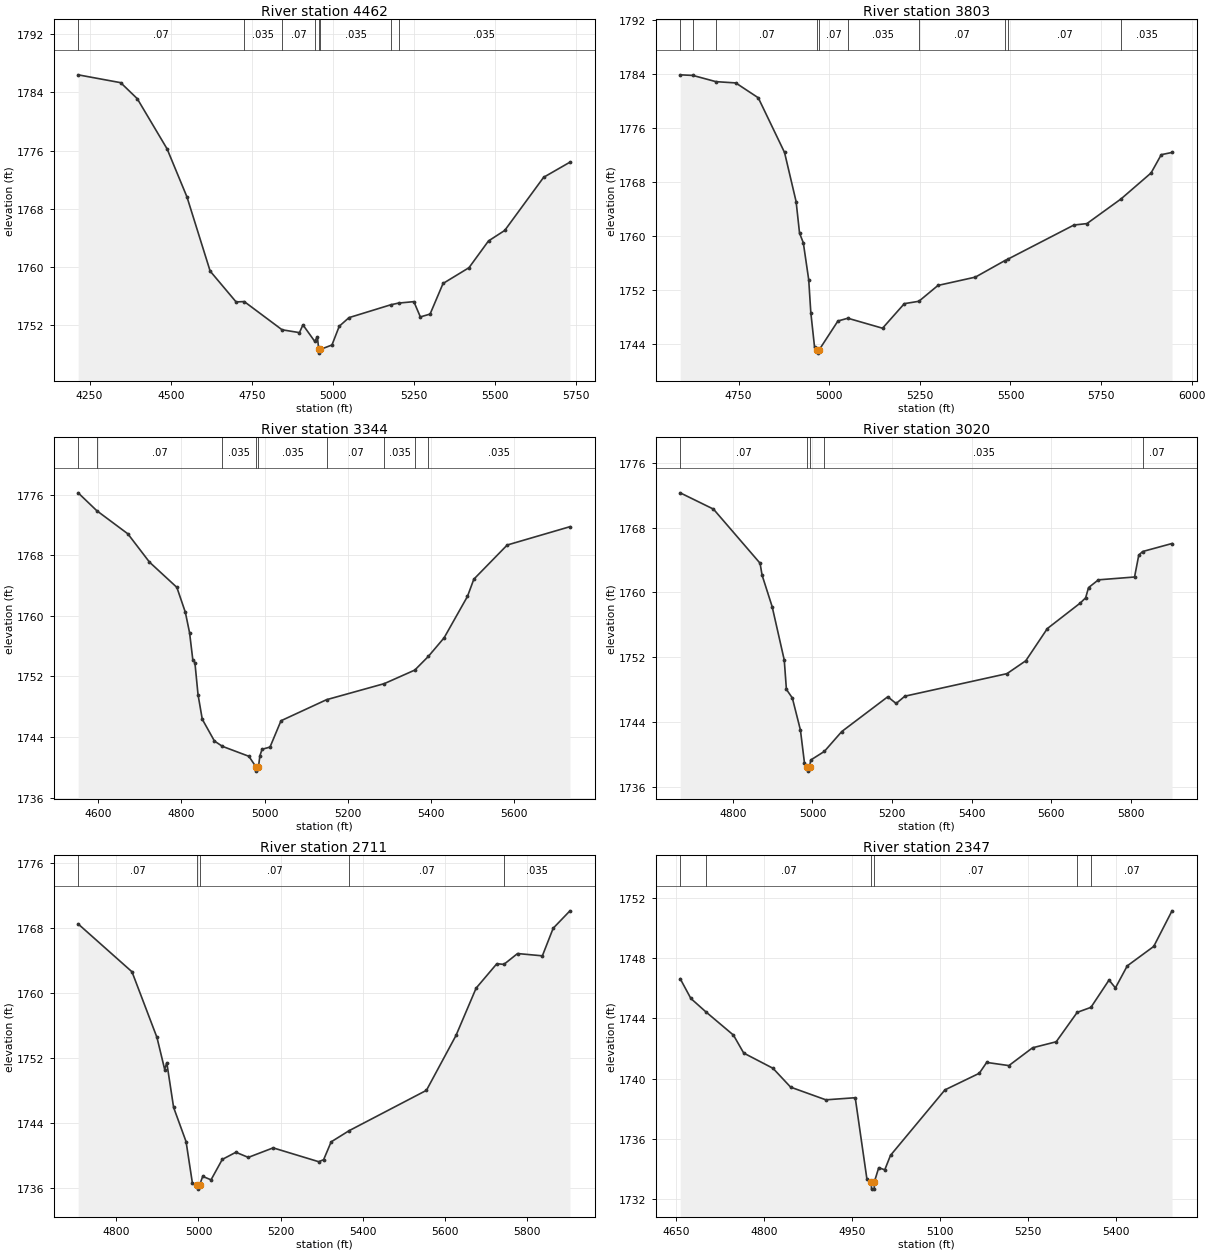
Type RM Length L Ch R = 1,4462,659,659,659
BEGIN DESCRIPTION:
Mapping XS 38ce88a5
END DESCRIPTION:
XS GIS Cut Line= 3
      1676040.20      6957219.53      1676200.79      6957992.08
      1676213.81      6958719.10
#Sta/Elev= 30
  4214.6 1786.43  4345.8 1785.35  4396.9 1783.15  4488.8 1776.25  4550.1 1769.64
  4621.6 1759.44  4701.6 1755.20  4726.7 1755.25  4843.3 1751.37  4896.9 1750.98
  4907.6 1752.05  4943.8 1749.79  4952.1 1750.40  4956.4 1748.66  4956.7 1748.16
  4960.8 1748.66  4997.1 1749.28  5019.6 1751.86  5049.6 1753.04  5178.6 1754.81
  5202.3 1755.04  5249.6 1755.24  5269.6 1753.14  5299.6 1753.53  5339.6 1757.74
  5419.6 1759.91  5479.7 1763.59  5529.7 1765.03  5649.7 1772.34  5730.8 1774.42
#Mann=8,-1,0
  4214.6    0.07       0  4726.7   0.035       0  4843.3    0.07       0
  4943.8   0.035       0  4956.4   0.035       0  4960.8   0.035       0
  5178.6    0.07       0  5202.3   0.035       0
Bank Sta=4956.4,4960.8
Exp/Cntr=0.3,0.1

Type RM Length L Ch R = 1,3803,459,459,459
BEGIN DESCRIPTION:
Mapping XS 07dd118b
END DESCRIPTION:
XS GIS Cut Line= 3
      1675558.42      6957479.90      1675664.76      6957877.06
      1675896.71      6958794.03
#Sta/Elev= 30
  4588.8 1783.90  4623.9 1783.81  4687.3 1782.89  4742.1 1782.70  4804.2 1780.50
  4876.7 1772.40  4908.6 1765.13  4918.1 1760.45  4928.5 1759.02  4943.4 1753.55
  4949.2 1748.68  4959.5 1743.56  4967.4 1743.17  4967.8 1742.67  4972.4 1743.17
  5024.0 1747.43  5051.4 1747.84  5147.1 1746.36  5207.2 1750.00  5247.3 1750.35
  5300.1 1752.70  5403.2 1753.93  5484.0 1756.36  5492.5 1756.58  5675.2 1761.65
  5711.0 1761.86  5805.0 1765.51  5888.0 1769.36  5916.1 1772.07  5945.8 1772.40
#Mann=10,-1,0
  4588.8    0.07       0  4623.9   0.035       0  4687.3    0.07       0
  4967.4    0.07       0  4972.4    0.07       0  5051.4   0.035       0
  5247.3    0.07       0  5484.0   0.035       0  5492.5    0.07       0
  5805.0   0.035       0
Bank Sta=4967.4,4972.4
Exp/Cntr=0.3,0.1

Type RM Length L Ch R = 1,3344,324,324,324
BEGIN DESCRIPTION:
Mapping XS 78a44c67
END DESCRIPTION:
XS GIS Cut Line= 3
      1675217.72      6957694.80      1675302.35      6958137.48
      1675449.63      6958854.41
#Sta/Elev= 30
  4551.8 1776.23  4596.9 1773.86  4671.3 1770.82  4723.4 1767.08  4789.2 1763.75
  4809.6 1760.46  4819.8 1757.75  4827.5 1754.21  4832.6 1753.81  4840.1 1749.59
  4850.3 1746.34  4879.6 1743.46  4898.8 1742.76  4962.3 1741.45  4980.2 1739.99
  4980.5 1739.49  4985.2 1739.99  4988.9 1741.52  4994.0 1742.37  5013.2 1742.67
  5039.6 1746.14  5149.1 1748.92  5287.9 1751.04  5361.3 1752.83  5394.0 1754.64
  5431.8 1757.09  5487.9 1762.55  5503.3 1764.83  5583.5 1769.34  5734.4 1771.76
#Mann=9,-1,0
  4551.8   0.035       0  4596.9    0.07       0  4898.8   0.035       0
  4980.2   0.035       0  4985.2   0.035       0  5149.1    0.07       0
  5287.9   0.035       0  5361.3    0.07       0  5394.0   0.035       0
Bank Sta=4980.2,4985.2
Exp/Cntr=0.3,0.1

Type RM Length L Ch R = 1,3020,309,309,309
BEGIN DESCRIPTION:
Mapping XS c133aad7
END DESCRIPTION:
XS GIS Cut Line= 3
      1674956.43      6957760.05      1675011.12      6958090.78
      1675287.17      6958947.59
#Sta/Elev= 30
  4667.8 1772.28  4751.4 1770.27  4868.4 1763.60  4873.5 1762.13  4898.8 1758.24
  4929.2 1751.66  4934.6 1748.04  4949.5 1746.98  4969.8 1743.03  4979.9 1738.99
  4987.5 1738.46  4987.9 1737.96  4992.6 1738.46  4995.7 1739.33  5029.9 1740.39
  5073.6 1742.84  5189.2 1747.13  5210.2 1746.30  5232.1 1747.20  5488.6 1749.98
  5535.9 1751.57  5590.0 1755.54  5672.5 1758.68  5686.2 1759.33  5693.5 1760.59
  5718.3 1761.55  5809.1 1761.90  5819.7 1764.60  5829.3 1765.04  5903.2 1766.03
#Mann=5,-1,0
  4667.8    0.07       0  4987.5    0.07       0  4992.6    0.07       0
  5029.9   0.035       0  5829.3    0.07       0
Bank Sta=4987.5,4992.6
Exp/Cntr=0.3,0.1

Type RM Length L Ch R = 1,2711,364,364,364
BEGIN DESCRIPTION:
Mapping XS 93fcddbc
END DESCRIPTION:
XS GIS Cut Line= 3
      1674763.72      6957848.62      1674716.85      6958142.86
      1674605.06      6959034.53
#Sta/Elev= 30
  4707.3 1768.47  4838.3 1762.59  4899.1 1754.52  4917.9 1750.58  4923.0 1751.42
  4939.6 1745.92  4969.9 1741.72  4985.2 1736.66  4997.7 1736.38  4998.1 1735.88
  5002.8 1736.38  5010.4 1737.45  5030.6 1737.02  5058.0 1739.53  5091.1 1740.41
  5121.3 1739.78  5181.8 1740.95  5292.6 1739.25  5304.6 1739.50  5322.9 1741.69
  5366.9 1743.07  5554.7 1748.02  5626.6 1754.76  5675.6 1760.58  5726.0 1763.58
  5743.2 1763.50  5776.4 1764.83  5836.8 1764.55  5863.1 1767.94  5903.9 1770.08
#Mann=5,-1,0
  4707.3    0.07       0  4997.7    0.07       0  5002.8    0.07       0
  5366.9    0.07       0  5743.2   0.035       0
Bank Sta=4997.7,5002.8
Exp/Cntr=0.3,0.1

Type RM Length L Ch R = 1,2347,392,392,392
BEGIN DESCRIPTION:
Mapping XS 3f9b63dc
END DESCRIPTION:
XS GIS Cut Line= 3
      1674384.64      6957939.85      1674405.47      6958283.57
      1674474.38      6958773.70
#Sta/Elev= 30
  4656.8 1746.62  4675.0 1745.31  4700.1 1744.44  4747.7 1742.88  4765.2 1741.69
  4815.2 1740.68  4845.3 1739.43  4905.4 1738.59  4955.5 1738.73  4975.5 1733.32
  4982.8 1733.17  4983.3 1732.67  4987.9 1732.67  4988.3 1733.17  4995.6 1734.09
  5005.9 1733.95  5015.7 1734.91  5108.6 1739.25  5167.2 1740.35  5179.8 1741.07
  5217.7 1740.86  5258.1 1742.04  5298.5 1742.44  5334.3 1744.39  5357.7 1744.72
  5388.6 1746.53  5399.5 1746.01  5419.7 1747.47  5464.9 1748.76  5496.1 1751.12
#Mann=6,-1,0
  4656.8   0.035       0  4700.1    0.07       0  4982.8    0.07       0
  4988.3    0.07       0  5334.3   0.035       0  5357.7    0.07       0
Bank Sta=4982.8,4988.3
Exp/Cntr=0.3,0.1

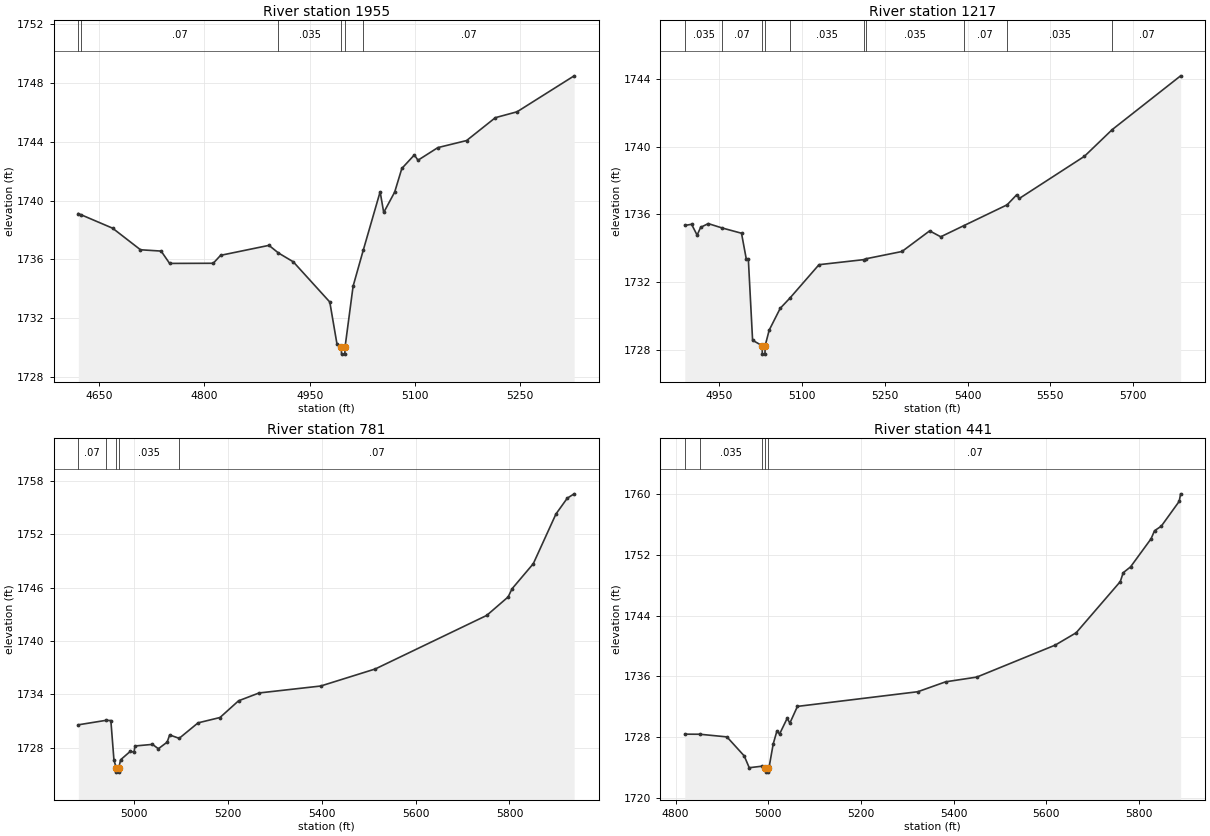
Type RM Length L Ch R = 1,1955,738,738,738
BEGIN DESCRIPTION:
Mapping XS 063cd4d8
END DESCRIPTION:
XS GIS Cut Line= 3
      1674191.94      6958072.59      1674091.67      6958439.82
      1674021.35      6958757.56
#Sta/Elev= 30
  4620.5 1739.12  4623.7 1739.05  4669.3 1738.12  4709.0 1736.65  4738.4 1736.56
  4750.5 1735.72  4812.6 1735.73  4823.1 1736.27  4892.0 1736.95  4905.5 1736.43
  4926.6 1735.83  4978.6 1733.09  4988.9 1730.21  4994.9 1730.04  4995.3 1729.54
  5000.0 1729.54  5000.4 1730.04  5011.8 1734.17  5026.2 1736.61  5050.3 1740.60
  5055.4 1739.19  5071.0 1740.58  5081.2 1742.19  5099.0 1743.11  5104.2 1742.75
  5132.5 1743.61  5173.4 1744.09  5214.4 1745.65  5245.3 1746.05  5326.6 1748.50
#Mann=6,-1,0
  4620.5   0.035       0  4623.7    0.07       0  4905.5   0.035       0
  4994.9   0.035       0  5000.4   0.035       0  5026.2    0.07       0
Bank Sta=4994.9,5000.4
Exp/Cntr=0.3,0.1

Type RM Length L Ch R = 1,1217,436,436,436
BEGIN DESCRIPTION:
Mapping XS 46143824
END DESCRIPTION:
XS GIS Cut Line= 3
      1673743.19      6957775.78      1673731.04      6957890.34
      1673793.53      6958671.55
#Sta/Elev= 30
  4887.3 1735.35  4899.6 1735.42  4909.6 1734.78  4916.1 1735.24  4929.8 1735.46
  4955.2 1735.20  4990.1 1734.89  4998.8 1733.36  5002.5 1733.36  5010.2 1728.56
  5027.4 1728.24  5027.9 1727.74  5032.6 1727.74  5033.0 1728.24  5040.3 1729.16
  5060.3 1730.45  5078.0 1731.06  5130.6 1733.03  5212.1 1733.33  5215.8 1733.38
  5281.0 1733.81  5331.2 1735.03  5351.3 1734.68  5392.6 1735.33  5471.6 1736.57
  5488.9 1737.16  5493.9 1736.95  5611.8 1739.44  5662.2 1741.02  5786.2 1744.20
#Mann=10,-1,0
  4887.3   0.035       0  4955.2    0.07       0  5027.4    0.07       0
  5033.0    0.07       0  5078.0   0.035       0  5212.1    0.07       0
  5215.8   0.035       0  5392.6    0.07       0  5471.6   0.035       0
  5662.2    0.07       0
Bank Sta=5027.4,5033
Exp/Cntr=0.3,0.1

Type RM Length L Ch R = 1,781,340,340,340
BEGIN DESCRIPTION:
Mapping XS a5922383
END DESCRIPTION:
XS GIS Cut Line= 3
      1673251.16      6957924.57      1673343.15      6958004.41
      1673693.84      6958870.72
#Sta/Elev= 30
  4881.4 1730.59  4940.0 1731.09  4950.7 1731.07  4957.3 1726.62  4962.1 1725.77
  4962.6 1725.27  4967.3 1725.27  4967.7 1725.77  4971.5 1726.66  4992.4 1727.62
  5000.0 1727.51  5002.1 1728.21  5039.4 1728.39  5051.9 1727.90  5070.6 1728.64
  5076.0 1729.45  5096.3 1729.07  5136.5 1730.81  5183.2 1731.41  5222.8 1733.29
  5266.4 1734.17  5397.7 1734.95  5514.1 1736.87  5751.5 1742.89  5797.2 1744.97
  5805.4 1745.88  5850.8 1748.71  5899.0 1754.29  5923.1 1756.07  5937.8 1756.56
#Mann=5,-1,0
  4881.4    0.07       0  4940.0   0.035       0  4962.1   0.035       0
  4967.7   0.035       0  5096.3    0.07       0
Bank Sta=4962.1,4967.7
Exp/Cntr=0.3,0.1

Type RM Length L Ch R = 1,441,0,0,0
BEGIN DESCRIPTION:
Chimney Creek 1140 1.0
END DESCRIPTION:
XS GIS Cut Line= 3
      1673030.01      6958013.03      1673070.20      6958188.49
      1673480.27      6958977.94
#Sta/Elev= 30
  4820.0 1728.42  4852.4 1728.41  4910.9 1728.06  4948.2 1725.56  4959.0 1724.01
  4986.5 1724.21  4993.9 1723.93  4994.4 1723.43  4999.1 1723.43  4999.5 1723.93
  5002.5 1724.30  5010.7 1727.13  5018.8 1728.85  5024.4 1728.43  5040.9 1730.51
  5046.6 1729.87  5063.0 1732.07  5322.8 1734.00  5382.6 1735.30  5449.8 1735.92
  5619.2 1740.13  5664.3 1741.75  5759.5 1748.48  5765.7 1749.64  5781.6 1750.41
  5825.8 1754.10  5833.3 1755.16  5847.9 1755.76  5886.5 1759.02  5889.6 1760.01
#Mann=5,-1,0
  4820.0    0.07       0  4852.4   0.035       0  4986.5    0.07       0
  4993.9    0.07       0  4999.5    0.07       0
Bank Sta=4993.9,4999.5
Exp/Cntr=0.3,0.1

Chan Stop Cuts=-1