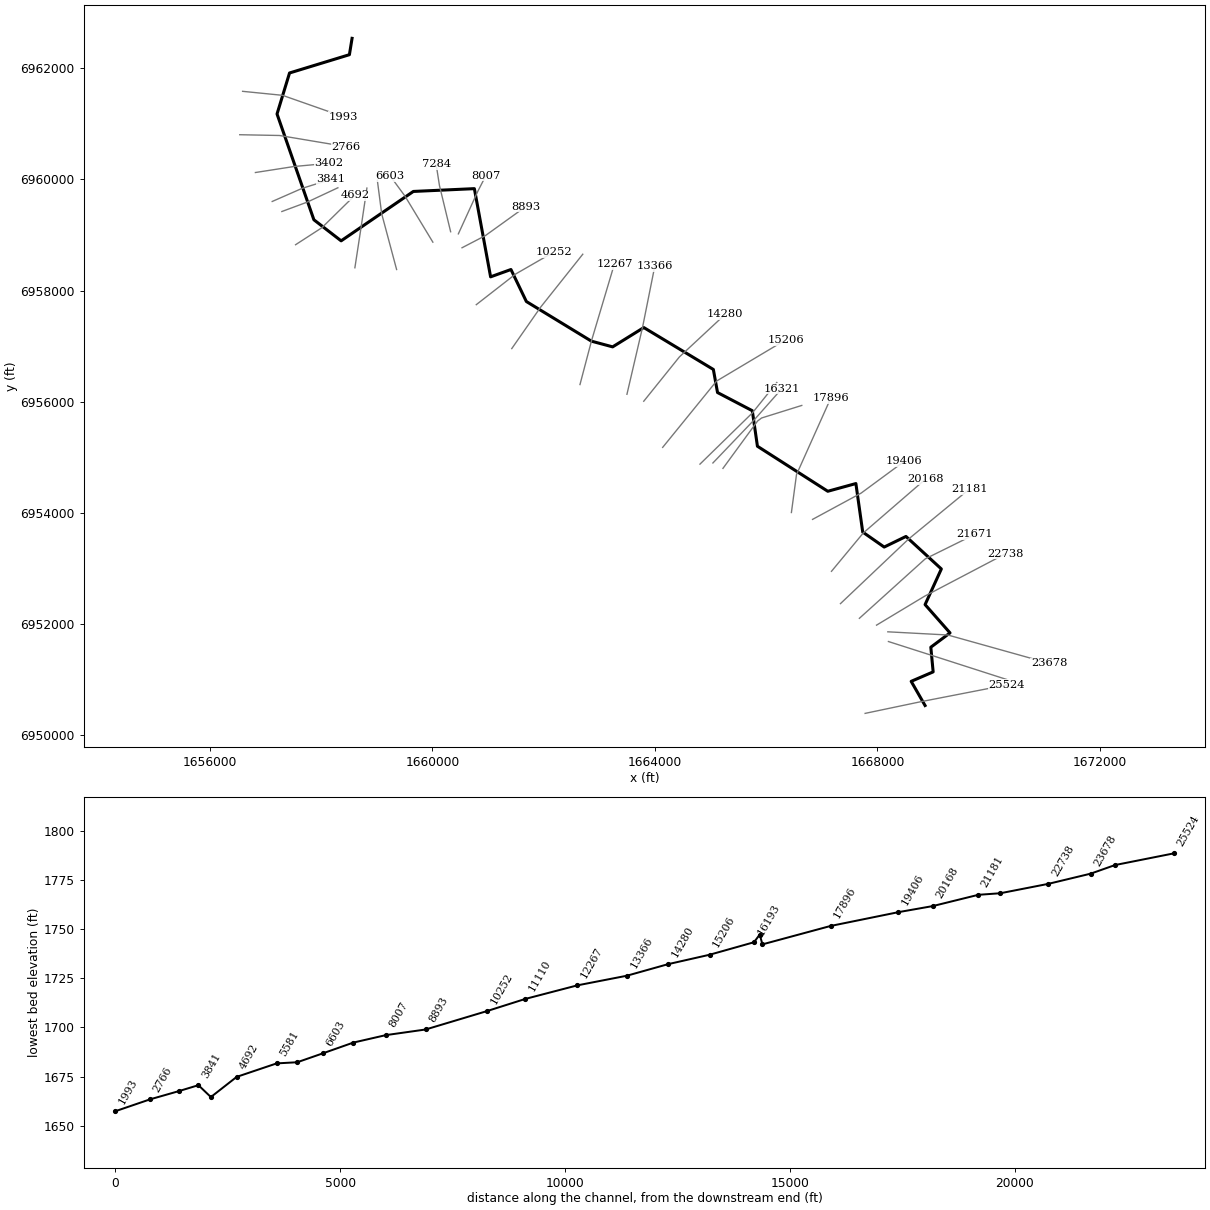
--- Chimney Creek 1141.prj (project) ---

Proj Title=Chimney Creek 1141 Base Level Engineering
Current Plan=p01
Default Exp/Contr=0.3,0.1
English Units
Geom File=g01
Flow File=f01
Plan File=p01
Y Axis Title=Elevation
X Axis Title(PF)=Main Channel Distance
X Axis Title(XS)=Station
BEGIN DESCRIPTION:
Chimney Creek 1141
END DESCRIPTION:
DSS Export Rating Curves= 0
DSS Export Rating Curve Sorted= 0
DSS Export Volume Flow Curves= 0
DXF OffsetX= 0
DXF OffsetY= 0
DXF ScaleX= 1
DXF ScaleY= 10

--- Chimney Creek 1141.p01 (plan) ---

Plan Title=Multiple Run
Short Identifier=Multiple
Geom File=g01
Flow File=f01
Subcritical Flow
K Sum by GR= 0
Std Step Tol= 0.01
Critical Tol= 0.01
Num of Std Step Trials= 20
Max Error Tol= 0.3
Flow Tol Ratio= 0.001
Split Flow NTrial= 30
Split Flow Tol= 0.02
Split Flow Ratio= 0.02
Log Output Level= 0
Friction Slope Method= 1
Unsteady Friction Slope Method= 2
Unsteady Bridges Friction Slope Method= 1
Parabolic Critical Depth
Global Vel Dist=  1 , 1 , 1
Global Log Level= 0
CheckData=True
Encroach Param= -1, 0, 0, 0
BEGIN DESCRIPTION:
Multiple Run
END DESCRIPTION:

--- Chimney Creek 1141.f01 (steady flow) ---

Flow Title=Multiple
Number of Profiles=7
Profile Names=10-year,25-year,50-year,1pct_min,100-year,1pct_plu,500-year
River Rch & RM= Chimney Creek 11,Reach-1,25524
     442     627     783     486     971    1936    1511
River Rch & RM= Chimney Creek 11,Reach-1,16381
     545     780     980     612    1221    2437    1920
River Rch & RM= Chimney Creek 11,Reach-1,6039
     605     871    1099     688    1374    2741    2175
Boundary for River Rch & Prof#=Chimney Creek 11,Reach-1,1
Up Type=0
Dn Type=3
Dn Slope=0.005
Boundary for River Rch & Prof#=Chimney Creek 11,Reach-1,2
Up Type=0
Dn Type=3
Dn Slope=0.005
Boundary for River Rch & Prof#=Chimney Creek 11,Reach-1,3
Up Type=0
Dn Type=3
Dn Slope=0.005
Boundary for River Rch & Prof#=Chimney Creek 11,Reach-1,4
Up Type=0
Dn Type=3
Dn Slope=0.005
Boundary for River Rch & Prof#=Chimney Creek 11,Reach-1,5
Up Type=0
Dn Type=3
Dn Slope=0.005
Boundary for River Rch & Prof#=Chimney Creek 11,Reach-1,6
Up Type=0
Dn Type=3
Dn Slope=0.005
Boundary for River Rch & Prof#=Chimney Creek 11,Reach-1,7
Up Type=0
Dn Type=3
Dn Slope=0.005

--- Chimney Creek 1141.g01 (geometry) ---

Geom Title=Existing Conditions
Program Version=4.10

River Reach=Chimney Creek 11,Reach-1
Reach XY= 30
        1668855.        6950538.      1668605.49      6950972.78
      1669000.38      6951143.09      1668958.53      6951586.55
      1669303.58      6951844.43      1668855.38      6952353.16
      1669147.66      6952994.33      1668511.74      6953578.87
      1668120.22      6953388.24       1667734.5      6953657.73
      1667611.44      6954530.32      1667106.45      6954391.53
      1665841.68      6955201.37      1665749.48      6955840.43
       1665124.4      6956167.35      1665049.41      6956582.39
      1663799.31      6957336.13      1663238.99      6956988.81
      1662856.58      6957091.83       1661688.2      6957804.42
      1661411.19      6958380.19      1661045.32      6958248.17
      1660753.55      6959834.47      1659656.58      6959784.17
      1658358.42      6958895.79      1657868.62      6959274.78
      1657206.22       6961177.5      1657431.17      6961914.87
      1658507.31      6962243.82        1658555.        6962538.

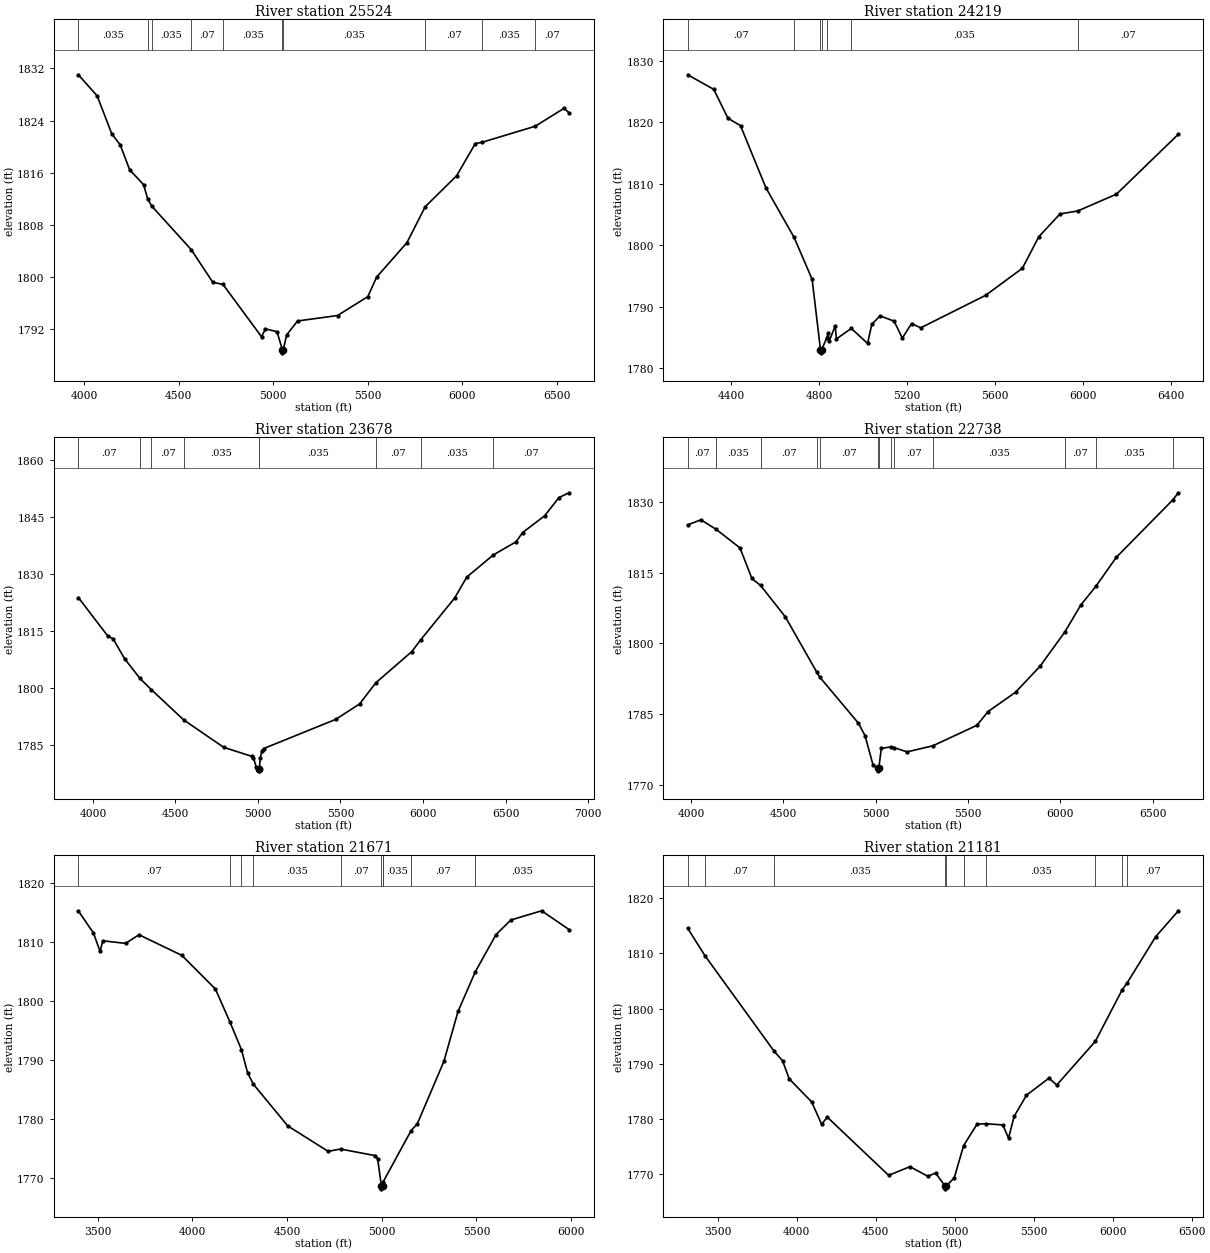
Type RM Length L Ch R = 1 ,25524   ,1305,1305,1305
BEGIN DESCRIPTION:
Chimney Creek 1141 53.0
END DESCRIPTION:
XS GIS Cut Line= 3
      1667777.74      6950396.74      1668785.01      6950608.04
      1670319.43      6950907.16
#Sta/Elev= 30
  3970.8 1831.02  4070.2 1827.78  4147.1 1821.97  4191.9 1820.27  4241.8 1816.46
  4315.4 1814.18  4336.7 1812.01  4357.9 1810.91  4567.5 1804.21  4680.7 1799.23
    4735 1798.89  4938.7 1790.87  4959.1 1792.08  5020.4 1791.65  5048.3 1788.91
  5048.7 1788.41  5053.5 1788.91  5071.3 1791.16  5128.9 1793.29  5340.4 1794.13
  5500.3 1797.03  5546.8 1800.02  5706.7 1805.29  5803.3  1810.8  5969.8 1815.56
  6067.9 1820.47  6104.4 1820.68  6384.3 1823.13  6537.4 1825.89  6563.3 1825.18
#Mann= 10 ,-1 , 0
  3970.8    .035       0  4336.7     .07       0  4357.9    .035       0
  4567.5     .07       0    4735    .035       0  5048.3    .035       0
  5053.5    .035       0  5803.3     .07       0  6104.4    .035       0
  6384.3     .07       0
Bank Sta=5048.3,5053.5
XS Rating Curve= 0 ,0
Exp/Cntr=0.3,0.1

Type RM Length L Ch R = 1 ,24219   ,541,541,541
BEGIN DESCRIPTION:
Mapping XS 4b5d072e
END DESCRIPTION:
XS GIS Cut Line= 3
      1668196.65      6951688.83      1668956.15      6951445.79
      1670319.04      6951007.41
#Sta/Elev= 30
  4203.8 1827.68  4322.1 1825.31  4386.4 1820.62  4443.6 1819.41  4559.1 1809.31
  4687.2 1801.24    4769 1794.44    4807 1782.99  4807.4 1782.49  4812.3 1782.99
  4834.9 1784.89  4841.8 1785.64  4847.1 1784.45    4874 1786.87  4879.2 1784.75
  4946.8 1786.46    5021 1784.02  5039.9  1787.1  5077.2  1788.5  5141.4 1787.64
  5178.8 1784.88  5220.6 1787.24  5262.6 1786.56  5556.8 1791.83  5724.2 1796.23
  5798.9 1801.36  5895.1 1805.07  5975.1 1805.54  6151.8 1808.28  6432.9 1818.02
#Mann= 7 ,-1 , 0
  4203.8     .07       0  4687.2    .035       0    4807    .035       0
  4812.3    .035       0  4834.9     .07       0  4946.8    .035       0
  5975.1     .07       0
Bank Sta=4807,4812.3
XS Rating Curve= 0 ,0
Exp/Cntr=0.3,0.1

Type RM Length L Ch R = 1 ,23678   ,940,940,940
BEGIN DESCRIPTION:
Mapping XS 88dc8e9f
END DESCRIPTION:
XS GIS Cut Line= 3
       1668185.8      6951863.76      1669263.88      6951806.47
      1671086.77      6951296.06
#Sta/Elev= 30
  3912.1 1823.74  4091.5 1813.55  4121.6 1812.95  4191.7 1807.67  4285.3 1802.45
  4354.2  1799.5  4549.8 1791.54  4792.5 1784.31  4962.8 1781.94  4972.8 1781.62
  4989.8 1779.08  5003.7 1778.62  5004.2 1778.12  5009.2 1778.62  5013.6 1781.41
    5024 1783.36  5034.4 1783.98  5470.6 1791.66  5615.9 1795.73  5713.9  1801.3
  5932.2 1809.52  5986.6 1812.65  6191.8 1823.63  6265.3 1829.14  6425.5 1834.96
  6564.2 1838.44  6603.5 1840.87  6737.5 1845.29  6823.8 1850.08  6884.7 1851.34
#Mann= 9 ,-1 , 0
  3912.1     .07       0  4285.3    .035       0  4354.2     .07       0
  4549.8    .035       0  5003.7    .035       0  5009.2    .035       0
  5713.9     .07       0  5986.6    .035       0  6425.5     .07       0
Bank Sta=5003.7,5009.2
XS Rating Curve= 0 ,0
Exp/Cntr=0.3,0.1

Type RM Length L Ch R = 1 ,22738   ,1067,1067,1067
BEGIN DESCRIPTION:
Mapping XS a4c60b5c
END DESCRIPTION:
XS GIS Cut Line= 3
      1667982.64      6951983.56      1668847.21      6952504.38
      1670305.53        6953270.
#Sta/Elev= 30
  3981.9 1825.14  4053.6  1826.2  4136.6 1824.16  4264.8 1820.24  4329.3 1813.76
  4376.4 1812.27    4510 1805.64    4681 1793.86    4696 1792.87  4906.1 1783.06
  4941.9 1780.42  4985.7 1774.13  5010.4 1773.45  5010.9 1772.95  5016.4 1773.45
  5029.8 1777.71  5084.5 1778.04  5098.5 1777.88  5169.4 1776.97  5309.6 1778.27
  5547.7 1782.61  5608.2 1785.53  5756.7 1789.62  5889.2 1795.13  6024.8 1802.47
  6109.7 1808.11  6190.9 1812.06  6302.5 1818.26  6608.3 1830.43  6638.3 1831.94
#Mann= 13 ,-1 , 0
  3981.9     .07       0  4136.6    .035       0  4376.4     .07       0
    4681    .035       0    4696     .07       0  5010.4     .07       0
  5016.4     .07       0  5084.5    .035       0  5098.5     .07       0
  5309.6    .035       0  6024.8     .07       0  6190.9    .035       0
  6608.3     .07       0
Bank Sta=5010.4,5016.4
XS Rating Curve= 0 ,0
Exp/Cntr=0.3,0.1

Type RM Length L Ch R = 1 ,21671   ,490,490,490
BEGIN DESCRIPTION:
Mapping XS 532ed27b
END DESCRIPTION:
XS GIS Cut Line= 3
       1667674.5      6952106.61       1668858.5      6953176.03
      1669750.38      6953616.76
#Sta/Elev= 30
  3398.7 1815.31  3478.2 1811.57  3513.3 1808.45  3527.5 1810.25  3647.8 1809.81
  3718.8 1811.27  3945.2 1807.77  4122.3 1802.06  4198.6 1796.49  4259.3 1791.81
    4292 1787.86  4322.8 1785.91  4504.3 1778.85  4717.2 1774.54  4782.6 1774.93
  4964.5 1773.82  4978.7 1773.26  4998.3 1768.68  4998.8 1768.18  5004.5 1768.68
  5006.3 1769.28  5154.9 1778.04    5188 1779.21  5328.2 1789.78    5403 1798.27
  5494.6 1805.02  5603.7  1811.3  5681.7 1813.77  5844.3 1815.34    5989 1812.16
#Mann= 10 ,-1 , 0
  3398.7     .07       0  4198.6    .035       0  4259.3     .07       0
  4322.8    .035       0  4782.6     .07       0  4998.3     .07       0
  5004.5     .07       0  5006.3    .035       0  5154.9     .07       0
  5494.6    .035       0
Bank Sta=4998.3,5004.5
XS Rating Curve= 0 ,0
Exp/Cntr=0.3,0.1

Type RM Length L Ch R = 1 ,21181   ,1013,1013,1013
BEGIN DESCRIPTION:
Mapping XS e9622179
END DESCRIPTION:
XS GIS Cut Line= 3
      1667334.19      6952370.47      1668556.41      6953530.19
       1669653.6      6954432.94
#Sta/Elev= 30
  3310.3 1814.51  3420.6 1809.51  3858.7 1792.23  3910.3 1790.57  3952.8 1787.27
  4094.4 1783.13  4157.9 1779.06  4193.5 1780.36  4582.2 1769.82  4716.9 1771.39
  4829.8 1769.66  4879.5 1770.23  4939.7 1767.88  4940.2 1767.38  4946.3 1767.88
  4997.4 1769.37  5056.9 1775.22  5141.7 1779.08  5197.9 1779.16  5304.6 1778.94
  5341.2 1776.56  5376.3 1780.47  5454.5 1784.32  5596.6  1787.4  5646.1 1786.16
  5890.5 1794.07  6060.3 1803.39  6093.5 1804.71  6271.7 1812.97    6416 1817.69
#Mann= 10 ,-1 , 0
  3310.3    .035       0  3420.6     .07       0  3858.7    .035       0
  4939.7    .035       0  4946.3    .035       0  5056.9     .07       0
  5197.9    .035       0  5890.5     .07       0  6060.3    .035       0
  6093.5     .07       0
Bank Sta=4939.7,4946.3
XS Rating Curve= 0 ,0
Exp/Cntr=0.3,0.1

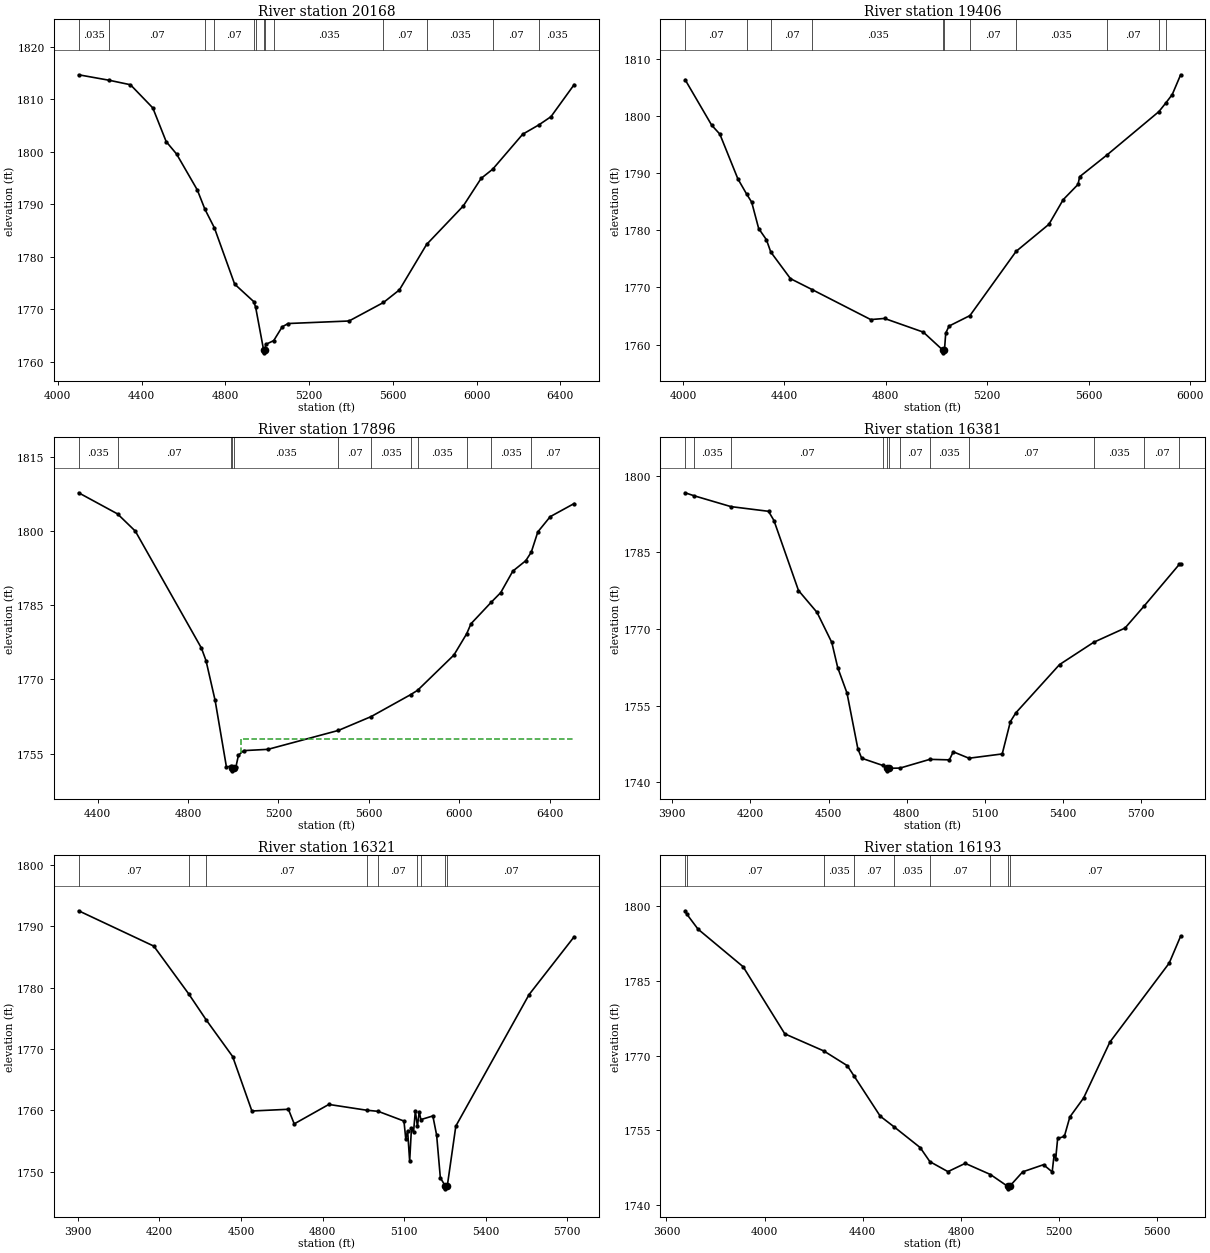
Type RM Length L Ch R = 1 ,20168   ,762,762,762
BEGIN DESCRIPTION:
Mapping XS a62ee3d5
END DESCRIPTION:
XS GIS Cut Line= 3
      1667172.73      6952951.72      1667745.65      6953642.69
      1668855.88      6954603.74
#Sta/Elev= 30
  4099.6 1814.67  4244.8 1813.63    4347 1812.77  4453.8 1808.35  4517.6 1801.93
  4567.1 1799.57  4666.3 1792.71  4702.3 1789.06    4748 1785.47  4844.5 1774.76
  4935.5 1771.43  4944.7 1770.37    4983 1762.16  4983.5 1761.66  4989.9 1762.16
  4992.8 1763.26    5031 1763.99  5071.6 1766.62  5100.1 1767.25  5390.7 1767.73
  5555.1 1771.26  5631.2 1773.66  5760.9 1782.32  5935.9 1789.65  6021.4 1794.92
  6076.6 1796.67  6219.9 1803.34  6297.5 1805.13  6354.8 1806.68  6465.6  1812.8
#Mann= 13 ,-1 , 0
  4099.6    .035       0  4244.8     .07       0  4702.3    .035       0
    4748     .07       0  4935.5    .035       0  4944.7     .07       0
    4983     .07       0  4989.9     .07       0    5031    .035       0
  5555.1     .07       0  5760.9    .035       0  6076.6     .07       0
  6297.5    .035       0
Bank Sta=4983,4989.9
XS Rating Curve= 0 ,0
Exp/Cntr=0.3,0.1

Type RM Length L Ch R = 1 ,19406   ,1510,1510,1510
BEGIN DESCRIPTION:
Mapping XS f76f3391
END DESCRIPTION:
XS GIS Cut Line= 3
      1666832.81      6953885.86      1667705.25      6954358.21
      1668480.62      6954929.67
#Sta/Elev= 30
  4007.9 1806.31  4112.7 1798.36    4145 1796.79  4216.3 1788.96  4250.4 1786.34
  4270.6 1784.91  4298.2  1780.3  4328.8 1778.34  4345.9  1776.2  4423.7 1771.54
  4510.5  1769.6  4740.4 1764.39  4794.7 1764.59  4947.8  1762.2  5024.2 1759.08
  5024.7 1758.58  5031.4 1759.08  5036.3 1762.03  5049.4 1763.26  5131.9 1765.09
    5314 1776.31  5443.5 1781.04  5499.8 1785.34  5558.4 1788.01  5564.6 1789.35
  5671.5 1793.11  5877.5 1800.73  5903.9 1802.19  5930.1 1803.71  5963.2 1807.16
#Mann= 11 ,-1 , 0
  4007.9     .07       0  4250.4    .035       0  4345.9     .07       0
  4510.5    .035       0  5024.2    .035       0  5031.4    .035       0
  5131.9     .07       0    5314    .035       0  5671.5     .07       0
  5877.5    .035       0  5903.9     .07       0
Bank Sta=5024.2,5031.4
XS Rating Curve= 0 ,0
Exp/Cntr=0.3,0.1

Type RM Length L Ch R = 1 ,17896   ,1515,1515,1515
BEGIN DESCRIPTION:
Mapping XS c363aed9
END DESCRIPTION:
XS GIS Cut Line= 3
      1666452.58      6954009.27      1666543.73      6954690.71
      1667159.22      6956064.74
#Sta/Elev= 30
  4315.8 1807.68  4487.9 1803.42  4566.7 1799.94  4859.3 1776.33  4879.5 1773.81
  4919.9 1765.76  4970.2 1752.27  4989.8 1752.58  4995.7 1752.06  4996.2 1751.56
  5003.2 1752.06  5011.3 1752.24  5023.2 1754.72  5046.4 1755.64  5153.7  1755.9
  5465.7 1759.72  5610.4 1762.51  5784.8 1766.93  5816.1 1767.82  5976.8 1774.94
  6033.1 1779.22  6052.3 1781.25  6142.1  1785.6  6183.7 1787.52  6237.4 1791.87
  6294.7 1793.97    6319 1795.69  6348.1 1799.79  6402.9 1802.86  6508.9 1805.51
#Mann= 12 ,-1 , 0
  4315.8    .035       0  4487.9     .07       0  4989.8    .035       0
  4995.7    .035       0  5003.2    .035       0  5465.7     .07       0
  5610.4    .035       0  5784.8     .07       0  5816.1    .035       0
  6033.1     .07       0  6142.1    .035       0    6319     .07       0
#XS Ineff= 2 , 0
       0                    5036       0    1758
Permanent Ineff=
       F       F
Bank Sta=4995.7,5003.2
XS Rating Curve= 0 ,0
Exp/Cntr=0.3,0.1

Type RM Length L Ch R = 1 ,16381   ,60,60,60
BEGIN DESCRIPTION:
Mapping XS 2f6771d2
END DESCRIPTION:
XS GIS Cut Line= 4
      1665221.98      6954803.29      1665843.49      6955653.96
      1665916.41      6955709.52      1666638.67      6955935.22
#Sta/Elev= 30
  3949.6 1796.67  3983.8 1796.09  4125.5 1793.96  4269.8 1793.04  4290.6 1791.24
  4384.8 1777.53  4455.9 1773.25  4512.7 1767.35  4535.4 1762.42    4571 1757.44
  4612.7 1746.53  4627.3 1744.68  4707.6 1743.28  4723.8 1742.71  4724.3 1742.21
  4731.6 1742.71  4774.4 1742.75    4889 1744.46    4964 1744.36  4978.7 1745.94
    5039 1744.68  5166.7 1745.52  5198.1 1751.86    5219 1753.57  5386.7 1763.02
  5517.9 1767.39  5637.9 1770.17  5710.4 1774.43    5846 1782.63  5851.5 1782.75
#Mann= 12 ,-1 , 0
  3949.6     .07       0  3983.8    .035       0  4125.5     .07       0
  4707.6    .035       0  4723.8    .035       0  4731.6    .035       0
  4774.4     .07       0    4889    .035       0    5039     .07       0
  5517.9    .035       0  5710.4     .07       0    5846    .035       0
Bank Sta=4723.8,4731.6
XS Rating Curve= 0 ,0
Exp/Cntr=0.3,0.1

Type RM Length L Ch R = 1 ,16321   ,128,128,128
BEGIN DESCRIPTION:
Mapping XS 5757be25
END DESCRIPTION:
XS GIS Cut Line= 3
       1665041.4      6954900.48      1665798.36      6955692.16
      1666280.52      6956236.77
#Sta/Elev= 30
    3903 1792.51  4179.5 1786.75  4307.7 1778.97    4373 1774.67  4469.5 1768.75
  4540.3 1759.87  4674.6 1760.15    4696 1757.77  4823.3 1760.94    4962    1760
  5005.1 1759.81  5099.6 1758.23  5106.3 1755.32    5113 1756.67  5120.6 1751.69
  5127.2 1757.07  5134.8 1756.39  5141.5 1759.87  5149.2 1757.35  5155.7 1759.73
  5161.9 1758.47  5205.9 1759.06  5219.8 1755.94  5233.5 1748.97  5251.3 1747.68
  5251.8 1747.18  5259.1 1747.68  5290.4 1757.41  5559.7 1778.84  5725.7 1788.28
#Mann= 9 ,-1 , 0
    3903     .07       0  4307.7    .035       0    4373     .07       0
    4962    .035       0  5005.1     .07       0  5149.2    .035       0
  5161.9     .07       0  5251.3    .035       0  5259.1     .07       0
Bank Sta=5251.3,5259.1
XS Rating Curve= 0 ,0
Exp/Cntr=0.3,0.1

Type RM Length L Ch R = 1 ,16193   ,987,987,987
BEGIN DESCRIPTION:
Mapping XS 5a4f7a00
END DESCRIPTION:
XS GIS Cut Line= 3
      1664808.79      6954879.68      1665753.22      6955803.27
      1666190.37      6956347.97
#Sta/Elev= 30
  3675.9 1799.05  3682.4 1798.41  3728.5 1795.37  3912.4 1787.83  4082.2 1774.37
  4241.2 1770.94  4336.8 1767.99  4364.5 1765.92  4471.1 1757.86  4527.1 1755.74
  4633.8 1751.57  4673.5 1748.74    4747 1746.74  4817.5  1748.4  4920.3 1746.16
  4990.5 1743.79    4991 1743.29  4998.4 1743.79  5051.7  1746.7  5136.5 1748.13
  5171.8 1746.69  5179.7 1750.11  5186.2 1749.36  5194.1 1753.39  5221.4  1753.8
  5243.8  1757.7  5299.8  1761.5    5407 1772.72  5648.6 1788.55  5695.3 1793.96
#Mann= 9 ,-1 , 0
  3675.9    .035       0  3682.4     .07       0  4241.2    .035       0
  4364.5     .07       0  4527.1    .035       0  4673.5     .07       0
  4920.3    .035       0  4990.5     .07       0  4998.4     .07       0
Bank Sta=4990.5,4998.4
XS Rating Curve= 0 ,0
Exp/Cntr=0.3,0.1

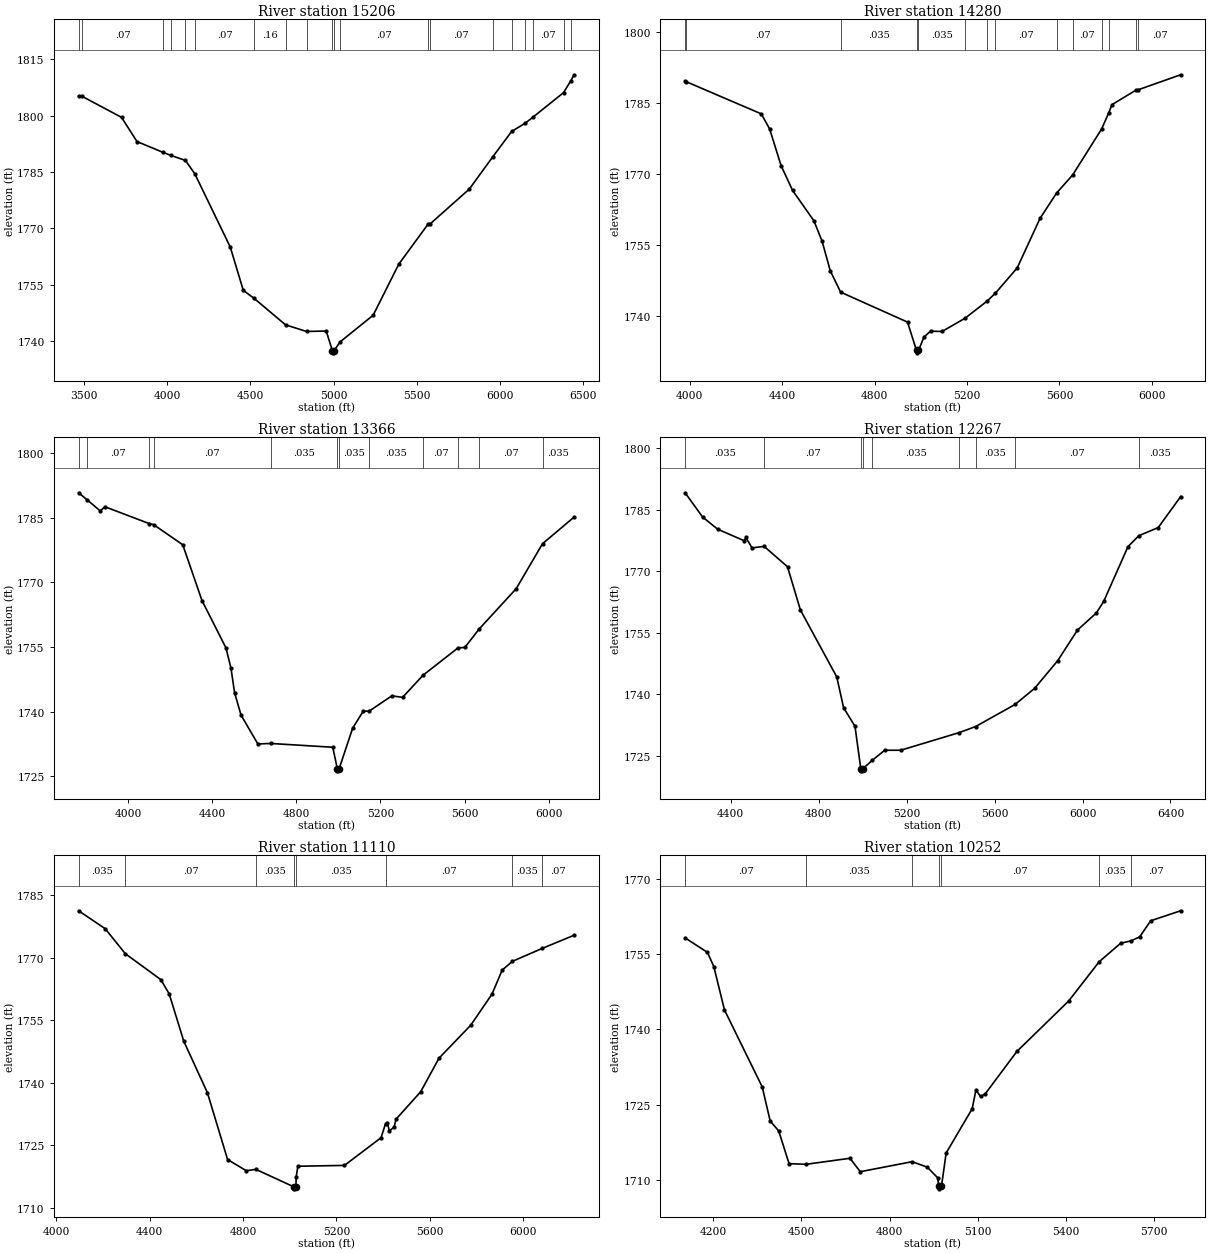
Type RM Length L Ch R = 1 ,15206   ,926,926,926
BEGIN DESCRIPTION:
Mapping XS 8a040908
END DESCRIPTION:
XS GIS Cut Line= 3
      1664138.48      6955181.01      1665107.24      6956373.73
      1666346.54      6957113.14
#Sta/Elev= 30
  3466.9  1805.2  3488.2  1805.1  3725.1 1799.52  3817.8 1793.09  3974.2 1790.22
  4020.3 1789.43    4109 1788.08  4165.7 1784.51  4378.8 1765.04  4457.1 1753.53
  4521.7 1751.43  4711.1 1744.38  4837.3 1742.62  4955.6 1742.74  4993.2 1737.44
  4993.7 1736.94  5001.3 1737.44  5040.3 1739.89  5237.9 1746.93  5391.7 1760.49
  5569.1  1771.2  5579.3 1771.16    5816 1780.46    5957 1789.03  6070.5 1795.77
  6150.3 1797.92  6197.7 1799.53    6383 1806.11  6424.6 1809.12  6446.6 1810.84
#Mann= 20 ,-1 , 0
  3466.9    .035       0  3488.2     .07       0  3974.2    .035       0
  4020.3     .07       0    4109    .035       0  4165.7     .07       0
  4521.7     .16       0  4711.1     .07       0  4837.3    .035       0
  4993.2    .035       0  5001.3    .035       0  5040.3     .07       0
  5569.1    .035       0  5579.3     .07       0    5957    .035       0
  6070.5     .07       0  6150.3    .035       0  6197.7     .07       0
    6383    .035       0  6424.6     .07       0
Bank Sta=4993.2,5001.3
XS Rating Curve= 0 ,0
Exp/Cntr=0.3,0.1

Type RM Length L Ch R = 1 ,14280   ,914,914,914
BEGIN DESCRIPTION:
Mapping XS 1b522786
END DESCRIPTION:
XS GIS Cut Line= 3
       1663798.2      6956010.87      1664438.84      6956807.75
      1665260.68      6957572.38
#Sta/Elev= 30
  3979.8 1789.51  3984.5 1789.41  4309.7 1782.61  4345.8 1779.42  4395.4 1771.67
    4445 1766.45  4537.8 1759.99    4573 1755.69  4608.2 1749.47    4653 1744.96
  4942.6 1738.63  4981.5 1732.64    4982 1732.14  4990.1 1732.64  5013.7 1735.48
  5042.1 1736.72  5091.9 1736.65  5191.4 1739.44  5286.4 1743.04  5323.2 1744.75
  5417.3 1750.07  5516.1 1760.53  5587.6 1765.87    5658 1769.75  5783.2 1779.46
  5813.9 1782.87  5827.7 1784.56  5931.2 1787.62    5942 1787.72  6124.8 1790.87
#Mann= 14 ,-1 , 0
  3979.8    .035       0  3984.5     .07       0    4653    .035       0
  4981.5    .035       0  4990.1    .035       0  5191.4     .07       0
  5286.4    .035       0  5323.2     .07       0  5587.6    .035       0
    5658     .07       0  5783.2    .035       0  5813.9     .07       0
  5931.2    .035       0    5942     .07       0
Bank Sta=4981.5,4990.1
XS Rating Curve= 0 ,0
Exp/Cntr=0.3,0.1

Type RM Length L Ch R = 1 ,13366   ,1099,1099,1099
BEGIN DESCRIPTION:
Mapping XS 8449814c
END DESCRIPTION:
XS GIS Cut Line= 3
      1663496.13       6956135.9      1663777.38      6957344.21
      1663996.12      6958437.95
#Sta/Elev= 30
  3765.1 1790.75  3806.2 1789.09  3867.6 1786.55  3890.5  1787.5    4102 1783.58
  4121.3 1783.37  4260.1  1778.7  4351.5 1765.77  4465.4  1754.8  4489.5 1750.05
  4506.5  1744.4  4537.3  1739.2  4617.3 1732.51  4677.6 1732.63  4973.4 1731.75
  4994.9 1726.78  4995.4 1726.28  5003.7 1726.78  5067.9 1736.17  5118.9 1740.17
  5145.1 1740.08  5254.3 1743.67  5305.3 1743.31    5402 1748.42  5569.2  1754.8
  5601.1 1754.88  5669.5 1759.17  5845.8 1768.54  5970.6 1778.94  6121.1 1785.13
#Mann= 12 ,-1 , 0
  3765.1    .035       0  3806.2     .07       0    4102    .035       0
  4121.3     .07       0  4677.6    .035       0  4994.9     .07       0
  5003.7    .035       0  5145.1    .035       0    5402     .07       0
  5569.2    .035       0  5669.5     .07       0  5970.6    .035       0
Bank Sta=4994.9,5003.7
XS Rating Curve= 0 ,0
Exp/Cntr=0.3,0.1

Type RM Length L Ch R = 1 ,12267   ,1157,1157,1157
BEGIN DESCRIPTION:
Mapping XS 36587b11
END DESCRIPTION:
XS GIS Cut Line= 3
      1662651.94      6956310.94      1662860.28       6957102.6
      1663270.01      6958477.63
#Sta/Elev= 30
  4192.8 1789.11  4272.5  1783.2    4341 1780.24    4462 1777.42    4469 1778.24
  4497.2 1775.68  4552.2 1776.06  4658.5 1771.09  4717.1 1760.57  4882.6 1744.25
  4913.6 1736.75  4965.3 1732.26  4991.8  1721.9  4992.3  1721.4  5000.8  1721.9
  5043.9 1723.96  5100.5 1726.41  5173.6 1726.42  5439.9 1730.72  5514.1 1732.19
  5693.4 1737.57  5782.4  1741.5  5887.1 1748.22    5977 1755.67  6063.4 1759.87
  6096.5 1762.68  6206.6 1775.98  6255.9 1778.65  6344.3 1780.64  6446.2 1788.17
#Mann= 9 ,-1 , 0
  4192.8    .035       0  4552.2     .07       0  4991.8     .07       0
  5000.8     .07       0  5043.9    .035       0  5439.9     .07       0
  5514.1    .035       0  5693.4     .07       0  6255.9    .035       0
Bank Sta=4991.8,5000.8
XS Rating Curve= 0 ,0
Exp/Cntr=0.3,0.1

Type RM Length L Ch R = 1 ,11110   ,858,858,858
BEGIN DESCRIPTION:
Mapping XS f473f152
END DESCRIPTION:
XS GIS Cut Line= 3
      1661425.96      6956957.93      1661942.45      6957700.12
      1662701.99      6958654.96
#Sta/Elev= 30
    4095 1781.31    4209    1777  4295.1    1771  4447.2 1764.78    4483 1761.38
  4545.9 1749.95  4647.1  1737.6  4733.5 1721.55  4813.8 1718.86  4854.7 1719.19
  5016.9 1715.01  5017.4 1714.51  5026.2 1715.01  5027.9 1717.47  5034.8 1719.94
  5234.6 1720.14  5391.5  1726.8  5410.5 1730.14  5418.7 1730.42  5426.8  1728.4
  5447.6 1729.36  5455.6 1731.24  5561.3 1737.83  5639.8 1745.89    5776 1753.83
  5867.2 1761.31  5910.5 1767.05  5954.4 1769.16  6082.2 1772.27  6219.3 1775.44
#Mann= 8 ,-1 , 0
    4095    .035       0  4295.1     .07       0  4854.7    .035       0
  5016.9    .035       0  5026.2    .035       0  5410.5     .07       0
  5954.4    .035       0  6082.2     .07       0
Bank Sta=5016.9,5026.2
XS Rating Curve= 0 ,0
Exp/Cntr=0.3,0.1

Type RM Length L Ch R = 1 ,10252   ,1359,1359,1359
BEGIN DESCRIPTION:
Mapping XS 3e02481c
END DESCRIPTION:
XS GIS Cut Line= 3
      1660787.92      6957747.84       1661495.4      6958299.07
      1662179.65      6958693.16
#Sta/Elev= 30
    4104 1758.23  4180.1 1755.34  4201.7 1752.52    4238 1743.89  4366.5 1728.57
  4393.6 1721.78  4422.6 1719.82  4457.8  1713.3  4515.2 1713.17    4665 1714.37
  4700.3  1711.7  4876.6 1713.69  4928.3  1712.6  4963.6 1710.49    4967 1708.79
  4967.5 1708.29  4976.5 1708.79  4992.5 1715.43  5081.2 1724.24  5093.7 1727.95
  5109.5 1726.67  5125.3 1727.18  5233.1 1735.62  5409.8 1745.69  5512.9 1753.46
  5586.5 1757.17  5621.7 1757.63  5651.2 1758.44  5688.5 1761.63  5790.5 1763.62
#Mann= 7 ,-1 , 0
    4104     .07       0  4515.2    .035       0  4876.6     .07       0
    4967     .07       0  4976.5     .07       0  5512.9    .035       0
  5621.7     .07       0
Bank Sta=4967,4976.5
XS Rating Curve= 0 ,0
Exp/Cntr=0.3,0.1

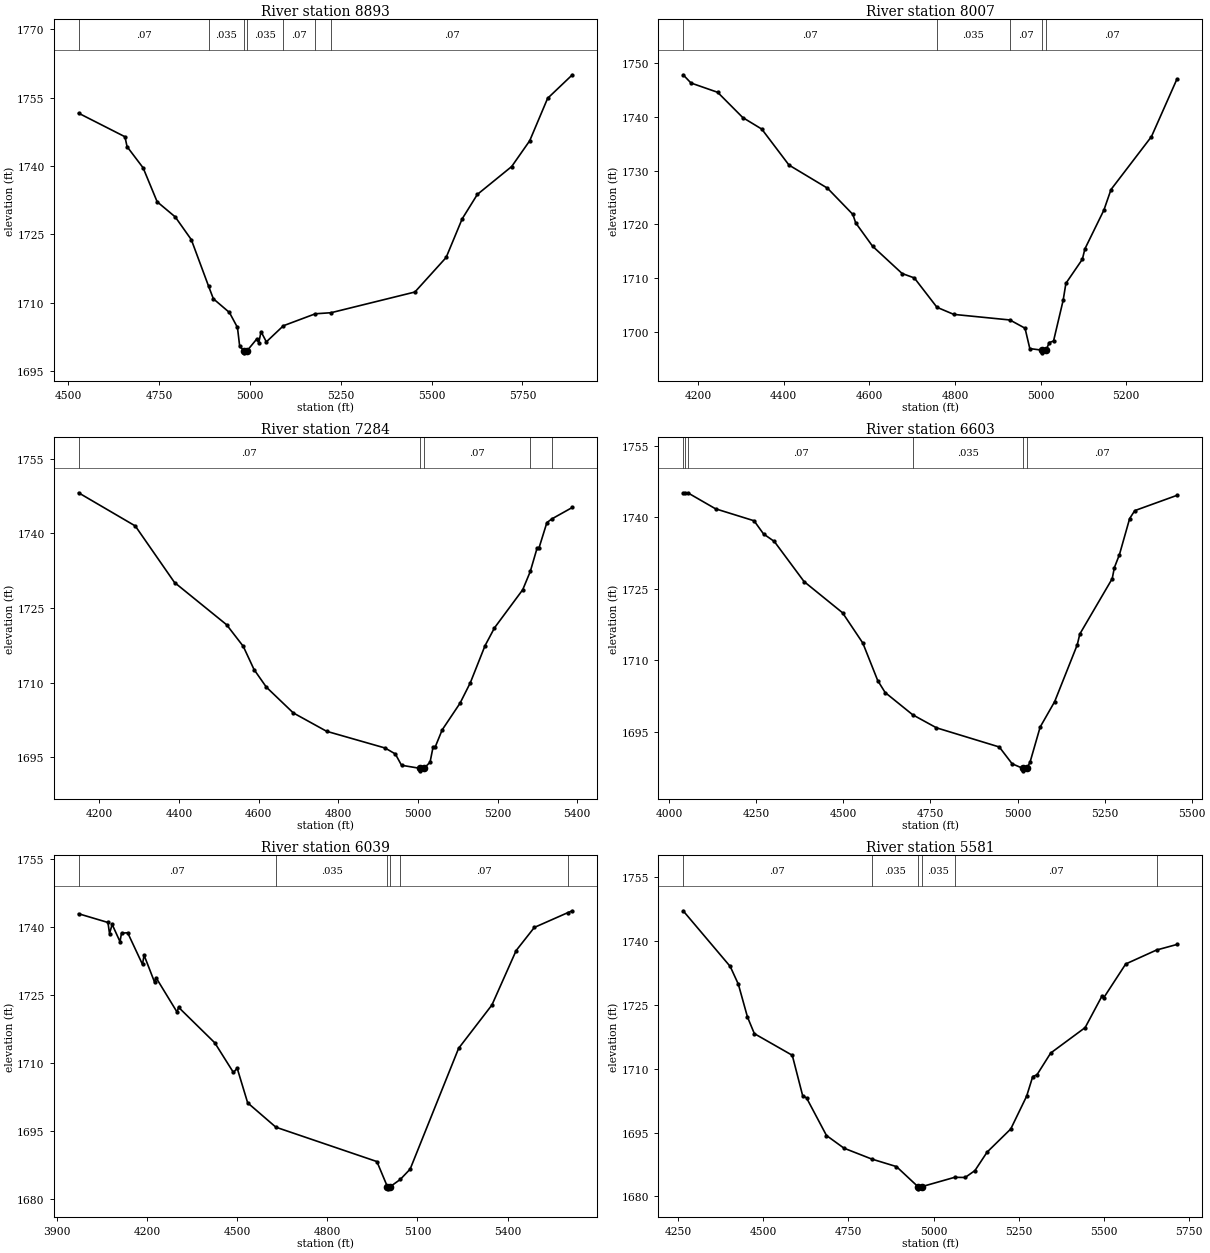
Type RM Length L Ch R = 1 ,8893    ,886,886,886
BEGIN DESCRIPTION:
Mapping XS 4c13cb3d
END DESCRIPTION:
XS GIS Cut Line= 3
      1660531.71      6958771.27      1660951.84      6958990.02
       1661670.3      6959507.17
#Sta/Elev= 30
  4528.5 1751.62  4656.2 1746.44    4662 1744.27  4706.2 1739.61  4744.8 1732.16
  4794.6 1728.83  4838.8 1723.84  4886.5 1713.58  4899.5 1710.85  4943.7 1707.84
  4965.8 1704.55  4971.9 1700.43  4983.1 1699.48  4983.6 1698.98  4992.7 1699.48
  5018.3 1701.96  5024.5 1701.23  5030.7 1703.63  5045.3 1701.39  5092.2 1704.93
  5180.2 1707.56  5223.2 1707.79  5454.1 1712.34    5540 1719.92  5584.1  1728.4
  5625.9 1733.77  5720.4  1739.9    5770 1745.56  5819.3 1754.88  5887.4 1760.05
#Mann= 7 ,-1 , 0
  4528.5     .07       0  4886.5    .035       0  4983.1    .035       0
  4992.7    .035       0  5092.2     .07       0  5180.2    .035       0
  5223.2     .07       0
Bank Sta=4983.1,4992.7
XS Rating Curve= 0 ,0
Exp/Cntr=0.3,0.1

Type RM Length L Ch R = 1 ,8007    ,723,723,723
BEGIN DESCRIPTION:
Mapping XS 4a8ef555
END DESCRIPTION:
XS GIS Cut Line= 3
      1660465.73      6959021.27      1660812.95      6959781.68
       1660957.9      6960064.68
#Sta/Elev= 30
  4164.8 1747.81  4183.2 1746.28  4245.5 1744.55  4304.1 1739.86  4348.6 1737.71
  4412.2 1731.02    4502 1726.73  4561.4 1721.85    4568 1720.28  4607.4 1715.94
  4676.5 1710.86    4705 1710.04  4757.9 1704.58  4797.2 1703.26  4928.4 1702.22
  4963.7 1700.69  4974.9  1696.9  5002.9 1696.61  5003.4 1696.11  5012.8 1696.61
  5020.4 1698.03  5030.3  1698.3  5052.8 1705.88  5059.2 1709.03  5097.7 1713.51
  5103.6 1715.44    5148 1722.65  5164.6 1726.47  5259.1 1736.31  5318.7 1747.01
#Mann= 5 ,-1 , 0
  4164.8     .07       0  4757.9    .035       0  4928.4     .07       0
  5002.9     .07       0  5012.8     .07       0
Bank Sta=5002.9,5012.8
XS Rating Curve= 0 ,0
Exp/Cntr=0.3,0.1

Type RM Length L Ch R = 1 ,7284    ,681,681,681
BEGIN DESCRIPTION:
Mapping XS cf4306d6
END DESCRIPTION:
XS GIS Cut Line= 3
      1660326.83       6959059.5      1660125.45      6959892.79
      1660066.43      6960271.23
#Sta/Elev= 30
  4147.6 1748.13  4290.1 1741.47  4388.7 1730.12  4519.4 1721.65  4561.3 1717.31
  4588.4 1712.65  4619.3 1709.12  4686.9 1703.95  4770.6 1700.26  4917.6  1696.9
  4943.2 1695.71  4958.8 1693.44  5005.2 1692.82  5005.7 1692.32  5015.1 1692.82
  5030.4 1694.04  5037.9 1697.05  5042.9 1697.01  5060.8 1700.53  5105.7 1705.89
  5131.6    1710  5168.5 1717.43  5192.3 1721.02  5263.2 1728.67  5282.2 1732.34
  5299.2    1737  5304.3 1737.11  5323.9 1742.15  5336.9 1742.91  5387.9 1745.19
#Mann= 5 ,-1 , 0
  4147.6     .07       0  5005.2     .07       0  5015.1     .07       0
  5282.2    .035       0  5336.9     .07       0
Bank Sta=5005.2,5015.1
XS Rating Curve= 0 ,0
Exp/Cntr=0.3,0.1

Type RM Length L Ch R = 1 ,6603    ,564,564,564
BEGIN DESCRIPTION:
Mapping XS 795c9257
END DESCRIPTION:
XS GIS Cut Line= 3
       1660007.4      6958871.95       1659507.4      6959698.35
      1659240.03      6960062.94
#Sta/Elev= 30
  4039.8  1745.1  4045.7 1745.13  4055.2 1745.04  4132.9 1741.77  4243.5 1739.26
  4270.7  1736.5  4301.7 1734.92  4387.1 1726.51  4497.6 1719.97  4555.8 1713.62
  4598.5 1705.77  4619.9 1703.25  4699.1 1698.58  4767.3 1695.85  4947.7 1691.83
  4984.5 1688.31    5016 1687.33  5016.5 1686.83    5026 1687.33  5035.7 1688.58
    5065 1696.01  5106.7 1701.35  5171.5 1713.25  5178.9 1715.52  5271.9 1727.12
  5278.1 1729.44  5292.7 1732.18    5322 1739.73  5336.7 1741.39  5457.8 1744.59
#Mann= 6 ,-1 , 0
  4039.8     .07       0  4045.7    .035       0  4055.2     .07       0
  4699.1    .035       0    5016    .035       0    5026     .07       0
Bank Sta=5016,5026
XS Rating Curve= 0 ,0
Exp/Cntr=0.3,0.1

Type RM Length L Ch R = 1 ,6039    ,458,458,458
BEGIN DESCRIPTION:
Mapping XS 0170c90d
END DESCRIPTION:
XS GIS Cut Line= 3
      1659355.72      6958379.95      1659087.48       6959382.6
      1659009.43      6959983.54
#Sta/Elev= 30
    3972 1742.96  4069.9 1741.03  4075.1 1738.59  4083.9  1740.6    4110 1736.81
  4115.1 1738.69  4135.6 1738.76  4184.9 1731.79  4190.1 1733.83  4224.9 1727.91
  4230.1 1728.86  4299.9 1721.29    4305 1722.34  4425.5 1714.52  4487.6 1707.98
  4500.1 1708.92    4535 1701.29    4629 1695.92  4965.2 1688.35    5000 1682.84
  5000.5 1682.34    5010 1682.84    5043 1684.41  5075.9 1686.69  5237.2  1713.3
  5348.1 1722.85  5428.8 1734.85  5489.3 1739.94  5600.5 1743.19  5615.9 1743.61
#Mann= 6 ,-1 , 0
    3972     .07       0    4629    .035       0    5000    .035       0
    5010    .035       0    5043     .07       0  5600.5    .035       0
Bank Sta=5000,5010
XS Rating Curve= 0 ,0
Exp/Cntr=0.3,0.1

Type RM Length L Ch R = 1 ,5581    ,889,889,889
BEGIN DESCRIPTION:
Mapping XS d913c680
END DESCRIPTION:
XS GIS Cut Line= 3
      1658605.71      6958411.26      1658717.68      6959143.01
      1658821.62      6959844.58
#Sta/Elev= 30
  4264.9 1747.14  4403.2 1734.04    4427 1729.87  4453.8 1722.15    4474 1718.25
  4585.3 1713.16  4615.7 1703.68  4627.3 1703.12  4685.7  1694.3  4737.1 1691.32
  4818.4 1688.77  4891.1 1686.99  4954.4 1682.26  4954.9 1681.76  4964.9 1682.26
    5062 1684.47  5092.7 1684.43  5121.4 1686.05  5157.1 1690.39  5226.6 1695.84
  5273.1 1703.53  5291.1 1708.17  5303.4 1708.56  5343.8 1713.69  5444.9 1719.67
  5494.5 1727.11  5499.6  1726.7    5564 1734.63  5654.4 1737.91  5714.4 1739.22
#Mann= 6 ,-1 , 0
  4264.9     .07       0  4818.4    .035       0  4954.4    .035       0
  4964.9    .035       0    5062     .07       0  5654.4    .035       0
Bank Sta=4954.4,4964.9
XS Rating Curve= 0 ,0
Exp/Cntr=0.3,0.1

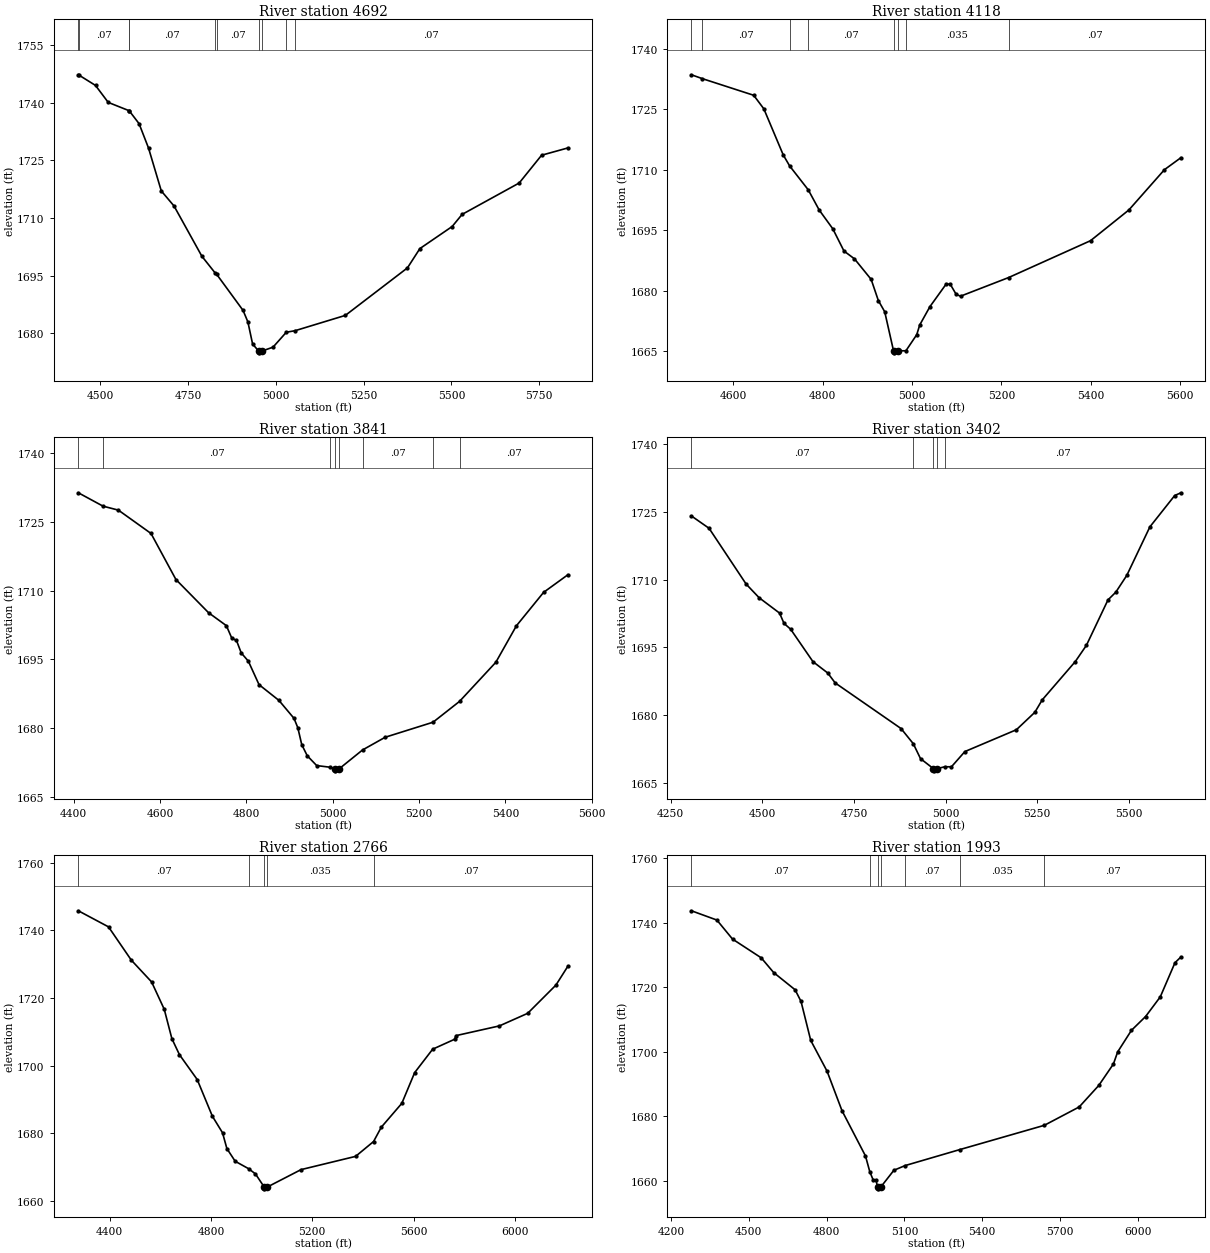
Type RM Length L Ch R = 1 ,4692    ,574,574,574
BEGIN DESCRIPTION:
Mapping XS c9a8be33
END DESCRIPTION:
XS GIS Cut Line= 3
      1657539.74      6958825.96      1658011.96      6959131.51
      1658604.77      6959713.93
#Sta/Elev= 30
  4437.9 1747.22  4440.1 1747.11  4486.8 1744.45    4523 1740.04  4581.8  1737.9
    4583 1737.83  4610.8 1734.51  4637.8 1728.15  4674.1 1717.01  4710.4 1713.09
  4789.6 1700.03  4826.7 1695.76  4831.5 1695.36  4906.9 1685.94  4920.6 1682.95
    4934  1677.2    4951 1675.41  4951.5 1674.91  4961.6 1675.41  4992.1 1676.38
    5030 1680.27  5054.6 1680.66  5198.1 1684.65  5374.8    1697  5410.2 1702.02
  5502.1 1707.76  5530.4 1710.91    5693 1719.08  5756.7  1726.3  5831.4 1728.19
#Mann= 10 ,-1 , 0
  4437.9    .035       0  4440.1     .07       0  4581.8    .035       0
    4583     .07       0  4826.7    .035       0  4831.5     .07       0
    4951     .07       0  4961.6     .07       0    5030    .035       0
  5054.6     .07       0
Bank Sta=4951,4961.6
XS Rating Curve= 0 ,0
Exp/Cntr=0.3,0.1

Type RM Length L Ch R = 1 ,4118    ,277,277,277
BEGIN DESCRIPTION:
Mapping XS 2e6a6d5c
END DESCRIPTION:
XS GIS Cut Line= 3
       1657293.2      6959423.17      1657751.54      6959593.32
      1658300.06      6959850.22
#Sta/Elev= 30
  4506.9 1733.57  4531.6  1732.6  4646.1 1728.49  4668.8 1725.13  4712.2  1713.7
  4726.6 1710.96  4768.1 1705.06  4792.6 1700.05    4823  1695.4    4848 1689.89
  4871.5 1687.95  4908.8 1682.86  4924.8 1677.63  4939.1 1674.84  4958.8 1665.16
  4959.3 1664.66  4969.5 1665.16  4986.5 1665.17  5010.7 1669.16  5017.4 1671.57
  5040.2 1676.11  5076.9 1681.77  5085.9 1681.61    5099 1679.13  5108.7  1678.7
  5216.2 1683.32  5399.3 1692.45  5485.1 1700.07  5564.6 1710.05  5601.5 1713.03
#Mann= 8 ,-1 , 0
  4506.9    .035       0  4531.6     .07       0  4726.6    .035       0
  4768.1     .07       0  4958.8    .035       0  4969.5     .07       0
  4986.5    .035       0  5216.2     .07       0
Bank Sta=4958.8,4969.5
XS Rating Curve= 0 ,0
Exp/Cntr=0.3,0.1

Type RM Length L Ch R = 1 ,3841    ,439,439,439
BEGIN DESCRIPTION:
Mapping XS a4aabc87
END DESCRIPTION:
XS GIS Cut Line= 3
      1657119.59      6959603.73      1657657.79      6959839.84
      1658178.52        6960003.
#Sta/Elev= 30
    4411 1731.37  4468.2 1728.45  4503.8 1727.58  4579.3 1722.49    4637 1712.44
  4712.5  1705.2  4753.8 1702.37  4766.3 1699.65  4777.2 1699.14  4788.2 1696.42
  4804.6 1694.63  4829.4  1689.5  4875.5 1686.06  4910.4 1682.14  4919.2  1680.1
  4928.3 1676.41  4941.1 1673.97  4962.9 1671.84  4993.7 1671.48    5005 1671.19
  5005.5 1670.69  5015.7 1671.19    5069 1675.24  5121.5 1678.02  5232.3  1681.3
  5293.6 1685.84  5377.7 1694.38  5425.4 1702.35  5488.3 1709.64  5544.4 1713.47
#Mann= 8 ,-1 , 0
    4411    .035       0  4468.2     .07       0  4993.7    .035       0
    5005    .035       0  5015.7    .035       0    5069     .07       0
  5232.3    .035       0  5293.6     .07       0
Bank Sta=5005,5015.7
XS Rating Curve= 0 ,0
Exp/Cntr=0.3,0.1

Type RM Length L Ch R = 1 ,3402    ,636,636,636
BEGIN DESCRIPTION:
Mapping XS d1254a42
END DESCRIPTION:
XS GIS Cut Line= 3
      1656817.49      6960124.56      1657508.48       6960232.2
      1658141.93      6960291.05
#Sta/Elev= 30
  4306.4 1724.13  4354.5  1721.4  4455.7 1709.03  4491.1 1706.01  4546.8 1702.61
    4559 1700.32  4577.1 1699.03  4637.9 1691.85  4678.3 1689.33  4698.6 1687.13
  4878.3 1677.02  4911.7 1673.66  4931.4 1670.35  4966.4 1668.15  4966.9 1667.65
  4977.2 1668.15  4997.4 1668.55  5015.8 1668.55  5052.4 1671.92    5193 1676.76
  5243.3 1680.62  5263.3 1683.36  5353.7 1691.87  5383.9 1695.45  5442.9 1705.54
  5464.2 1707.24  5494.3 1710.98  5557.2 1721.72  5624.9 1728.66  5641.9 1729.27
#Mann= 5 ,-1 , 0
  4306.4     .07       0  4911.7    .035       0  4966.4     .07       0
  4977.2    .035       0  4997.4     .07       0
Bank Sta=4966.4,4977.2
XS Rating Curve= 0 ,0
Exp/Cntr=0.3,0.1

Type RM Length L Ch R = 1 ,2766    ,773,773,773
BEGIN DESCRIPTION:
Mapping XS c27784bd
END DESCRIPTION:
XS GIS Cut Line= 3
      1656535.89      6960804.43      1657251.19      6960790.54
      1658451.31      6960589.36
#Sta/Elev= 30
  4276.6 1745.82  4395.7 1741.06  4485.8  1731.2  4565.8 1724.76  4615.8 1716.65
  4645.8 1707.98  4675.8 1703.21  4745.8 1695.87  4805.8 1684.99  4845.8  1680.1
    4863 1675.42  4895.8 1671.66  4948.6 1669.47  4975.8 1667.92  5010.7    1664
  5011.2  1663.5  5021.6    1664  5155.8 1669.19  5371.1 1673.11  5442.1 1677.51
  5472.5 1681.74  5553.6 1688.81  5604.3 1697.91  5675.3 1704.84  5762.5  1707.8
  5767.5 1708.86  5938.9 1711.74  6050.4 1715.46  6161.9 1723.82  6208.9 1729.38
#Mann= 5 ,-1 , 0
  4276.6     .07       0  4948.6    .035       0  5010.7    .035       0
  5021.6    .035       0  5442.1     .07       0
Bank Sta=5010.7,5021.6
XS Rating Curve= 0 ,0
Exp/Cntr=0.3,0.1

Type RM Length L Ch R = 1 ,1993    ,654,654,654
BEGIN DESCRIPTION:
Mapping XS ad732d98
END DESCRIPTION:
XS GIS Cut Line= 3
      1656587.38       6961584.9      1657304.99        6961513.
      1658405.09      6961126.57
#Sta/Elev= 30
  4278.8 1743.71  4376.9 1740.83  4437.2 1734.93  4547.8 1729.12  4595.9 1724.54
  4678.4 1719.21  4701.3  1715.6  4738.7  1703.5  4801.7 1693.95  4859.3 1681.69
  4949.8 1667.66  4966.4 1662.77  4979.9 1660.13    4990 1660.11  4997.2 1657.96
  4997.7 1657.46  5008.2 1657.96  5059.3 1663.22  5102.8 1664.68  5312.4 1669.61
  5639.5 1677.17  5773.7 1682.86  5849.1 1689.52  5905.7 1696.19  5922.1 1699.94
  5975.1 1706.62  6029.7 1710.91  6086.3    1717    6143  1727.6    6166 1729.39
#Mann= 7 ,-1 , 0
  4278.8     .07       0  4966.4    .035       0  4997.2    .035       0
  5008.2    .035       0  5102.8     .07       0  5312.4    .035       0
  5639.5     .07       0
Bank Sta=4997.2,5008.2
XS Rating Curve= 0 ,0
Exp/Cntr=0.3,0.1