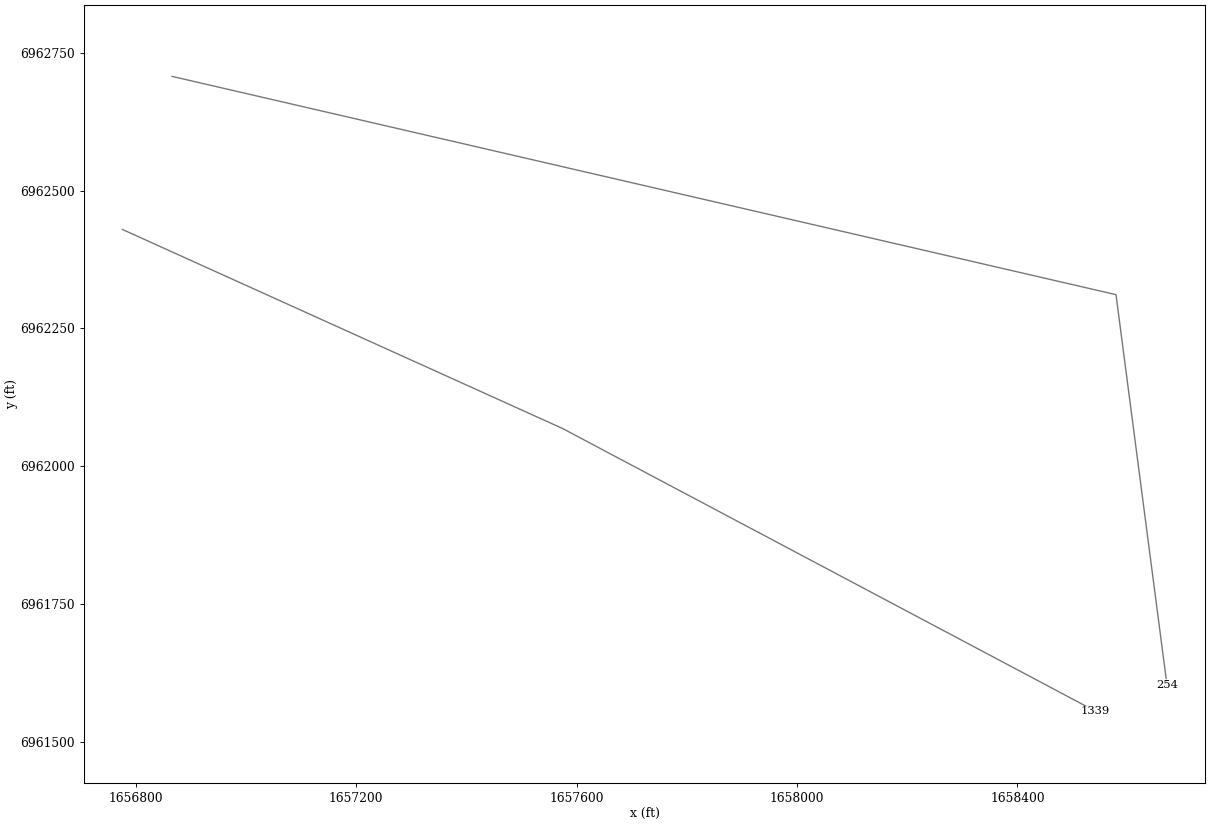
HEC-RAS study Chimney Creek 1141.prj: Chimney Creek 1141 Base Level Engineering

--- Chimney Creek 1141.g01 (geometry) --- (continued)

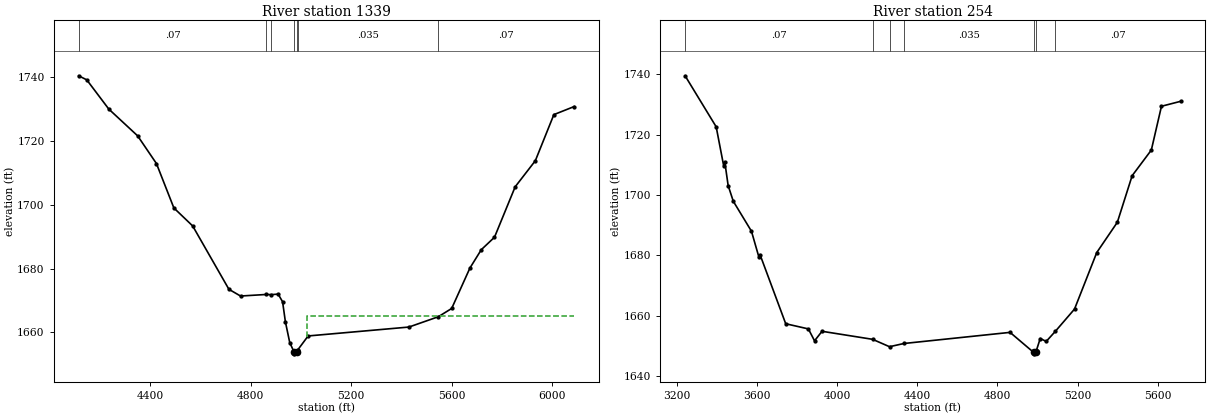
Type RM Length L Ch R = 1 ,1339    ,1085,1085,1085
BEGIN DESCRIPTION:
Mapping XS 42819684
END DESCRIPTION:
XS GIS Cut Line= 3
      1656775.47      6962429.44      1657574.11      6962068.32
      1658541.45      6961555.18
#Sta/Elev= 30
  4115.3 1740.46  4147.7 1739.18  4235.5    1730  4350.1 1721.62  4424.9 1712.93
  4494.2 1699.01    4569 1693.37  4713.2  1673.5  4759.4 1671.39  4862.7 1671.88
  4881.3 1671.82    4909 1671.99  4926.7  1669.6  4937.9  1663.3  4955.2 1656.79
  4972.8 1653.76  4973.3 1653.26  4983.9 1653.76  4987.6 1654.55  5028.4 1658.87
  5429.3 1661.66  5546.2 1664.89  5599.5 1667.49    5672 1680.16  5717.3 1685.92
  5769.8 1689.83  5852.1 1705.65  5932.3 1713.82    6006 1728.28  6086.8 1730.81
#Mann= 7 ,-1 , 0
  4115.3     .07       0  4862.7    .035       0  4881.3     .07       0
  4972.8    .035       0  4983.9     .07       0  4987.6    .035       0
  5546.2     .07       0
#XS Ineff= 2 , 0
       0                    5025       0    1665
Permanent Ineff=
       F       F
Bank Sta=4972.8,4983.9
XS Rating Curve= 0 ,0
Exp/Cntr=0.3,0.1

Type RM Length L Ch R = 1 ,254     ,0,0,0
BEGIN DESCRIPTION:
Chimney Creek 1141 1.0
END DESCRIPTION:
XS GIS Cut Line= 3
      1656865.77      6962707.21      1658578.86      6962311.07
      1658671.33      6961603.08
#Sta/Elev= 30
  3241.7 1739.47  3396.8 1722.56  3434.4 1709.56  3439.5 1711.02  3456.5  1703.1
  3482.2 1697.89  3572.8 1687.97  3610.4 1679.28  3615.5 1680.22  3743.7 1657.32
  3856.7 1655.61  3887.5 1651.66  3924.8 1654.82  4177.1 1652.16  4261.6 1649.71
  4333.7 1650.78    4863 1654.46  4980.2 1647.85  4980.7 1647.35  4991.4 1647.85
  5013.5 1652.43  5043.4 1651.47  5088.7 1654.79  5184.6 1662.18  5295.6 1680.92
  5398.2 1690.94  5472.1 1706.37  5567.8 1714.86  5618.3 1729.37    5714 1731.01
#Mann= 7 ,-1 , 0
  3241.7     .07       0  4177.1    .035       0  4261.6     .07       0
  4333.7    .035       0  4980.2    .035       0  4991.4    .035       0
  5088.7     .07       0
Bank Sta=4980.2,4991.4
XS Rating Curve= 0 ,0
Exp/Cntr=0.3,0.1

Chan Stop Cuts=-1
Use User Specified Reach Order=0
Composite Channel Slope=5