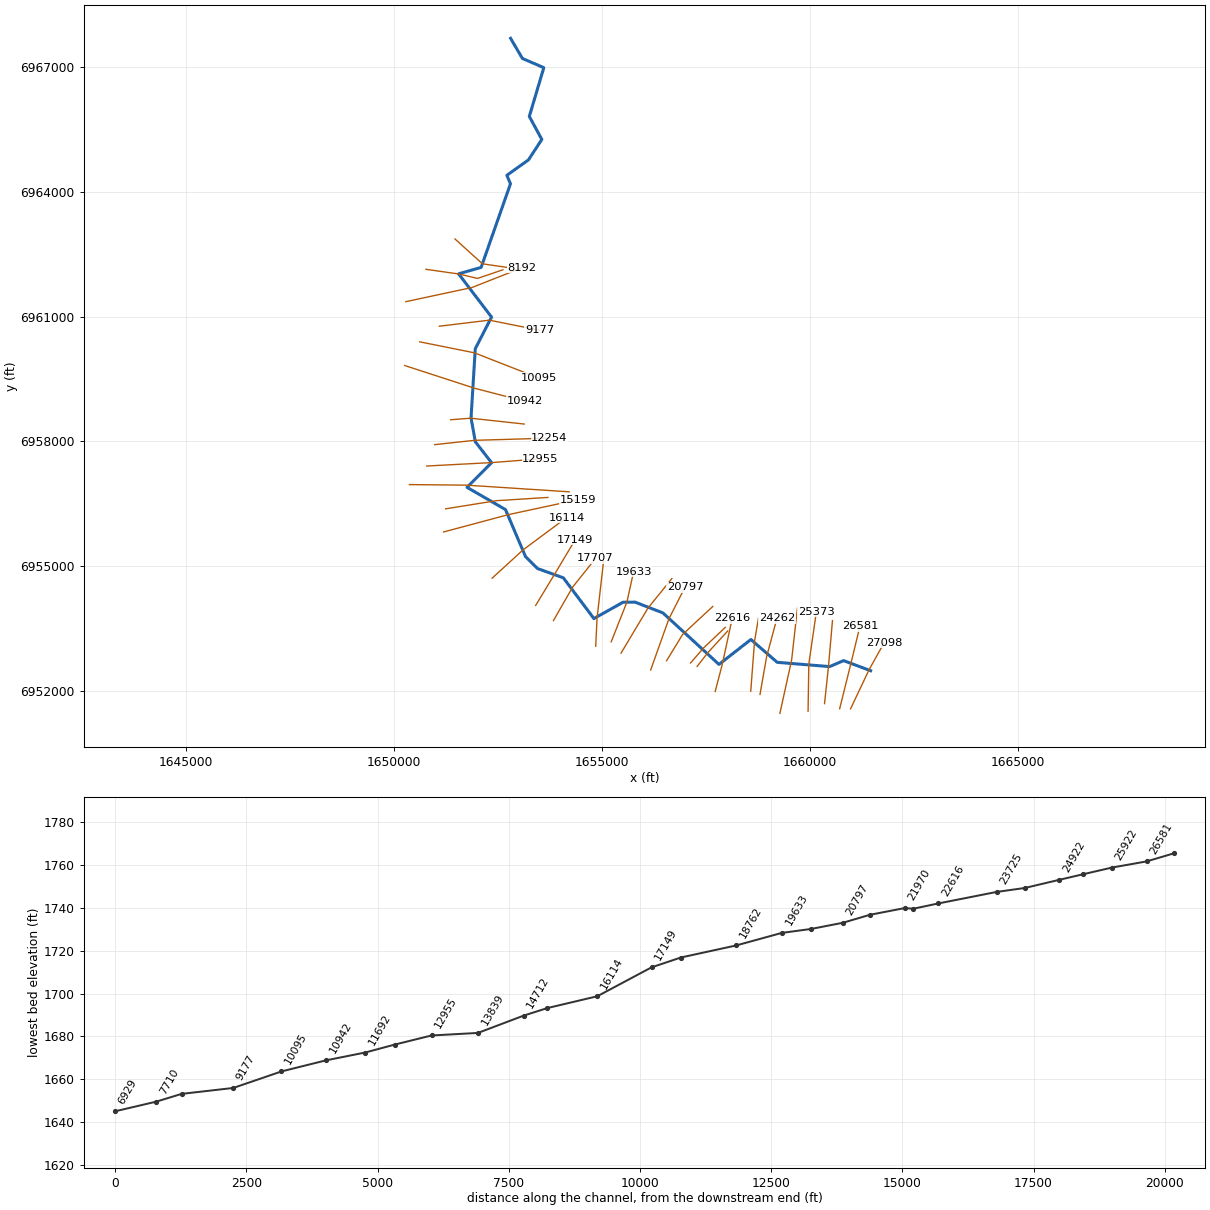
--- Chimney Creek 1142.prj (project) ---

Proj Title=Chimney Creek 1142 Base Level Engineering
Current Plan=p01
Default Exp/Contr=0.3,0.1
English Units
Geom File=g01
Flow File=f01
Plan File=p01
BEGIN DESCRIPTION:
Chimney Creek 1142
END DESCRIPTION:

--- Chimney Creek 1142.p01 (plan) ---

Plan Title=Multiple Run
Short Identifier=Multiple
Geom File=g01
Flow File=f01
Subcritical Flow
K Sum by GR= 0
Std Step Tol= 0.01
Critical Tol= 0.01
Num of Std Step Trials= 20
Max Error Tol= 0.3
Flow Tol Ratio= 0.001
Split Flow NTrial= 30
Split Flow Tol= 0.02
Split Flow Ratio= 0.02
Log Output Level= 0
Friction Slope Method= 1
Unsteady Friction Slope Method= 2
Unsteady Bridges Friction Slope Method= 1
Parabolic Critical Depth
Global Vel Dist=  1 , 1 , 1
Global Log Level= 0
CheckData=True
Encroach Param= -1, 0, 0, 0
BEGIN DESCRIPTION:
Multiple Run
END DESCRIPTION:

--- Chimney Creek 1142.f01 (steady flow) ---

Flow Title=Multiple
Number of Profiles=7
Profile Names=10-year,25-year,50-year,1pct_min,100-year,1pct_plu,500-year
River Rch & RM= Chimney Creek 11,Reach-1,27098
     243     335     412     252     503    1003     759
River Rch & RM= Chimney Creek 11,Reach-1,26581
     356     500     619     382     761    1519    1167
River Rch & RM= Chimney Creek 11,Reach-1,17707
     484     690     865     539    1075    2145    1682
River Rch & RM= Chimney Creek 11,Reach-1,10095
     580     835    1052     659    1315    2623    2081
River Rch & RM= Chimney Creek 11,Reach-1,4180
     631     910    1151     722    1441    2875    2291
River Rch & RM= Chimney Creek 11,Reach-1,3338
     761    1107    1407     888    1771    3534    2844
Boundary for River Rch & Prof#=Chimney Creek 11,Reach-1,1
Up Type=0
Dn Type=3
Dn Slope=0.005
Boundary for River Rch & Prof#=Chimney Creek 11,Reach-1,2
Up Type=0
Dn Type=3
Dn Slope=0.005
Boundary for River Rch & Prof#=Chimney Creek 11,Reach-1,3
Up Type=0
Dn Type=3
Dn Slope=0.005
Boundary for River Rch & Prof#=Chimney Creek 11,Reach-1,4
Up Type=0
Dn Type=3
Dn Slope=0.005
Boundary for River Rch & Prof#=Chimney Creek 11,Reach-1,5
Up Type=0
Dn Type=3
Dn Slope=0.005
Boundary for River Rch & Prof#=Chimney Creek 11,Reach-1,6
Up Type=0
Dn Type=3
Dn Slope=0.005
Boundary for River Rch & Prof#=Chimney Creek 11,Reach-1,7
Up Type=0
Dn Type=3
Dn Slope=0.005

--- Chimney Creek 1142.g01 (geometry) ---

Geom Title=Existing Conditions

River Reach=Chimney Creek 11,Reach-1
Reach XY= 30
      1661455.00      6952488.00      1660805.11      6952730.69
      1660470.37      6952587.23      1659210.97      6952690.14
      1658577.84      6953238.29      1657810.86      6952640.05
      1656464.98      6953877.32      1655794.50      6954136.80
      1655506.55      6954134.25      1654806.56      6953741.74
      1654071.75      6954721.54      1653452.70      6954943.83
      1653165.52      6955228.21      1652681.99      6956361.47
      1651757.92      6956895.97      1652347.92      6957488.00
      1651958.61      6957989.50      1651854.60      6958563.00
      1651956.22      6960227.50      1652347.50      6960988.00
      1651555.55      6962027.37      1652096.86      6962181.94
      1652802.74      6964193.56      1652713.96      6964394.67
      1653234.61      6964766.78      1653555.11      6965258.08
      1653254.68      6965810.81      1653602.66      6966982.51
      1653088.30      6967204.64      1652805.00      6967688.00

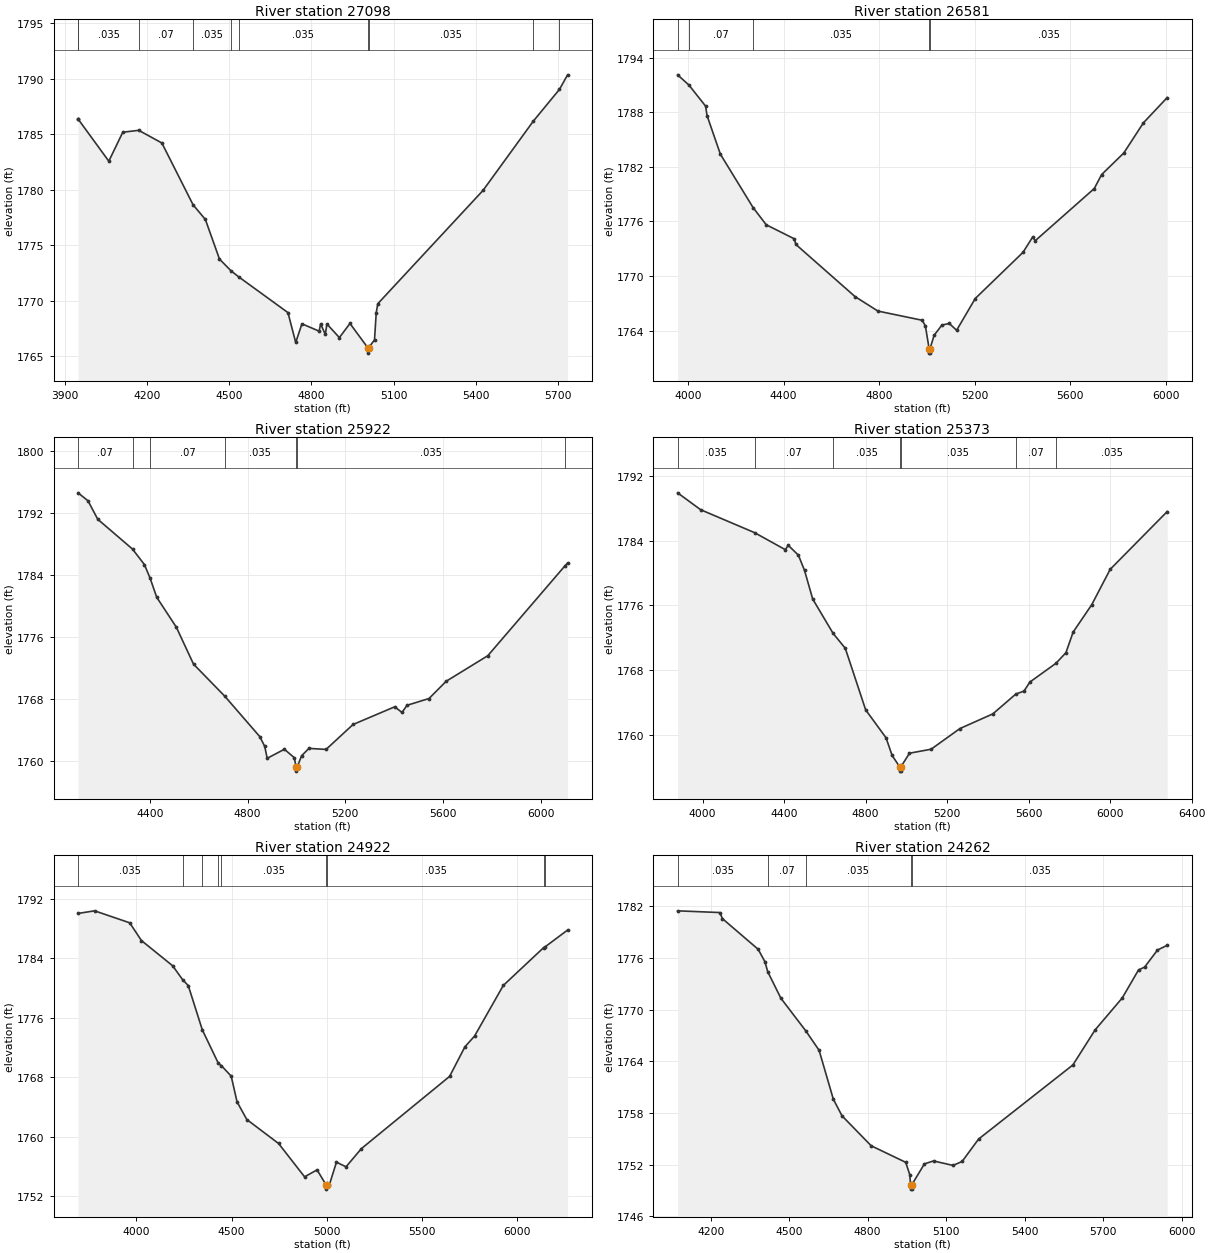
Type RM Length L Ch R = 1,27098,517,517,517
BEGIN DESCRIPTION:
Chimney Creek 1142 52.0
END DESCRIPTION:
XS GIS Cut Line= 3
      1660971.87      6951571.66      1661421.83      6952521.36
      1661779.98      6953162.97
#Sta/Elev= 30
  3949.1 1786.38  3949.9 1786.34  4061.4 1782.56  4112.4 1785.17  4170.6 1785.34
  4254.9 1784.20  4368.8 1778.63  4413.6 1777.31  4465.1 1773.74  4507.0 1772.69
  4534.6 1772.15  4714.8 1768.92  4743.1 1766.23  4765.8 1767.91  4828.5 1767.25
  4834.0 1767.90  4851.2 1766.95  4856.8 1767.90  4902.3 1766.67  4941.0 1767.94
  5005.6 1765.77  5005.9 1765.27  5009.6 1765.77  5030.5 1766.46  5036.8 1768.91
  5042.5 1769.72  5426.4 1779.93  5609.5 1786.16  5705.1 1789.03  5734.8 1790.34
#Mann=10,-1,0
  3949.1    0.07       0  3949.9   0.035       0  4170.6    0.07       0
  4368.8   0.035       0  4507.0    0.07       0  4534.6   0.035       0
  5005.6   0.035       0  5009.6   0.035       0  5609.5    0.07       0
  5705.1   0.035       0
Bank Sta=5005.6,5009.6
Exp/Cntr=0.3,0.1

Type RM Length L Ch R = 1,26581,659,659,659
BEGIN DESCRIPTION:
Mapping XS a8ac4baa
END DESCRIPTION:
XS GIS Cut Line= 3
      1660710.13      6951574.23      1660962.74      6952589.85
      1661199.30      6953564.70
#Sta/Elev= 30
  3956.3 1792.11  4003.9 1790.98  4073.5 1788.67  4079.4 1787.64  4135.4 1783.39
  4272.2 1777.53  4327.3 1775.64  4444.5 1774.10  4451.3 1773.48  4699.2 1767.75
  4794.9 1766.16  4980.3 1765.15  4993.7 1764.52  5009.2 1762.04  5009.4 1761.54
  5013.0 1761.54  5013.3 1762.04  5030.2 1763.50  5062.7 1764.62  5093.6 1764.80
  5124.4 1764.05  5202.4 1767.54  5402.3 1772.61  5443.4 1774.32  5453.1 1773.88
  5700.7 1779.62  5731.6 1781.16  5824.2 1783.52  5906.5 1786.84  6006.0 1789.61
#Mann=5,-1,0
  3956.3   0.035       0  4003.9    0.07       0  4272.2   0.035       0
  5009.2   0.035       0  5013.3   0.035       0
Bank Sta=5009.2,5013.3
Exp/Cntr=0.3,0.1

Type RM Length L Ch R = 1,25922,549,549,549
BEGIN DESCRIPTION:
Mapping XS 4dd6963d
END DESCRIPTION:
XS GIS Cut Line= 3
      1660346.85      6951697.51      1660442.34      6952595.93
      1660537.78      6953693.51
#Sta/Elev= 30
  4105.3 1794.55  4146.0 1793.53  4186.2 1791.14  4328.5 1787.30  4377.3 1785.30
  4401.0 1783.51  4427.6 1781.09  4508.0 1777.23  4578.4 1772.47  4705.7 1768.36
  4850.0 1763.12  4870.1 1761.86  4880.1 1760.33  4950.5 1761.50  4991.2 1760.41
  4998.7 1759.18  4999.0 1758.68  5002.9 1759.18  5020.9 1760.66  5051.0 1761.61
  5121.3 1761.48  5231.7 1764.69  5402.3 1766.97  5432.4 1766.24  5452.5 1767.16
  5542.9 1768.04  5613.1 1770.26  5783.8 1773.56  6100.2 1785.16  6110.5 1785.50
#Mann=7,-1,0
  4105.3    0.07       0  4328.5   0.035       0  4401.0    0.07       0
  4705.7   0.035       0  4998.7   0.035       0  5002.9   0.035       0
  6100.2    0.07       0
Bank Sta=4998.7,5002.9
Exp/Cntr=0.3,0.1

Type RM Length L Ch R = 1,25373,451,451,451
BEGIN DESCRIPTION:
Mapping XS 05cca831
END DESCRIPTION:
XS GIS Cut Line= 3
      1659951.89      6951515.20      1659969.25      6952648.01
      1660151.27      6953904.86
#Sta/Elev= 30
  3877.0 1789.89  3989.8 1787.81  4254.7 1784.98  4405.6 1782.88  4419.9 1783.42
  4469.9 1782.20  4499.9 1780.32  4539.9 1776.80  4640.3 1772.55  4699.9 1770.72
  4799.9 1763.13  4899.9 1759.68  4929.9 1757.50  4967.7 1756.07  4968.0 1755.57
  4971.8 1755.57  4972.1 1756.07  5015.1 1757.78  5121.1 1758.27  5262.5 1760.82
  5424.2 1762.63  5537.2 1765.08  5577.1 1765.44  5606.1 1766.56  5733.6 1768.86
  5782.8 1770.17  5818.3 1772.72  5909.2 1776.08  6000.2 1780.46  6279.9 1787.58
#Mann=7,-1,0
  3877.0   0.035       0  4254.7    0.07       0  4640.3   0.035       0
  4967.7   0.035       0  4972.1   0.035       0  5537.2    0.07       0
  5733.6   0.035       0
Bank Sta=4967.7,4972.1
Exp/Cntr=0.3,0.1

Type RM Length L Ch R = 1,24922,660,660,660
BEGIN DESCRIPTION:
Mapping XS 849911d9
END DESCRIPTION:
XS GIS Cut Line= 3
      1659274.80      6951463.10      1659556.92      6952747.84
      1659695.78      6953993.27
#Sta/Elev= 30
  3694.7 1790.02  3781.6 1790.37  3965.9 1788.76  4027.3 1786.38  4191.2 1782.99
  4243.2 1781.13  4273.1 1780.33  4346.8 1774.38  4431.1 1769.88  4446.8 1769.57
  4498.3 1768.17  4529.0 1764.71  4580.2 1762.34  4746.9 1759.12  4883.4 1754.64
  4948.8 1755.58  4997.7 1753.49  4998.0 1752.99  5002.2 1753.49  5012.6 1753.51
  5050.5 1756.61  5100.8 1755.99  5181.3 1758.43  5644.1 1768.13  5724.6 1772.11
  5774.9 1773.54  5925.9 1780.35  6138.0 1785.44  6146.1 1785.55  6263.2 1787.79
#Mann=9,-1,0
  3694.7   0.035       0  4243.2    0.07       0  4346.8   0.035       0
  4431.1    0.07       0  4446.8   0.035       0  4997.7   0.035       0
  5002.2   0.035       0  6138.0    0.07       0  6146.1   0.035       0
Bank Sta=4997.7,5002.2
Exp/Cntr=0.3,0.1

Type RM Length L Ch R = 1,24262,537,537,537
BEGIN DESCRIPTION:
Mapping XS 3f672efe
END DESCRIPTION:
XS GIS Cut Line= 3
      1658797.11      6951919.20      1658955.97      6952828.05
      1659203.13      6953743.86
#Sta/Elev= 30
  4073.6 1781.46  4234.8 1781.26  4245.0 1780.55  4381.4 1777.00  4407.4 1775.55
  4418.1 1774.39  4468.3 1771.32  4563.8 1767.52  4614.3 1765.28  4668.7 1759.61
  4701.8 1757.68  4813.4 1754.20  4945.4 1752.28  4961.1 1750.83  4963.8 1749.67
  4964.2 1749.17  4968.2 1749.17  4968.5 1749.67  5016.9 1752.10  5051.6 1752.44
  5126.2 1751.92  5161.0 1752.38  5224.0 1754.98  5584.4 1763.58  5669.4 1767.65
  5773.0 1771.35  5835.2 1774.60  5858.5 1774.93  5907.7 1776.91  5944.8 1777.46
#Mann=5,-1,0
  4073.6   0.035       0  4418.1    0.07       0  4563.8   0.035       0
  4963.8   0.035       0  4968.5   0.035       0
Bank Sta=4963.8,4968.5
Exp/Cntr=0.3,0.1

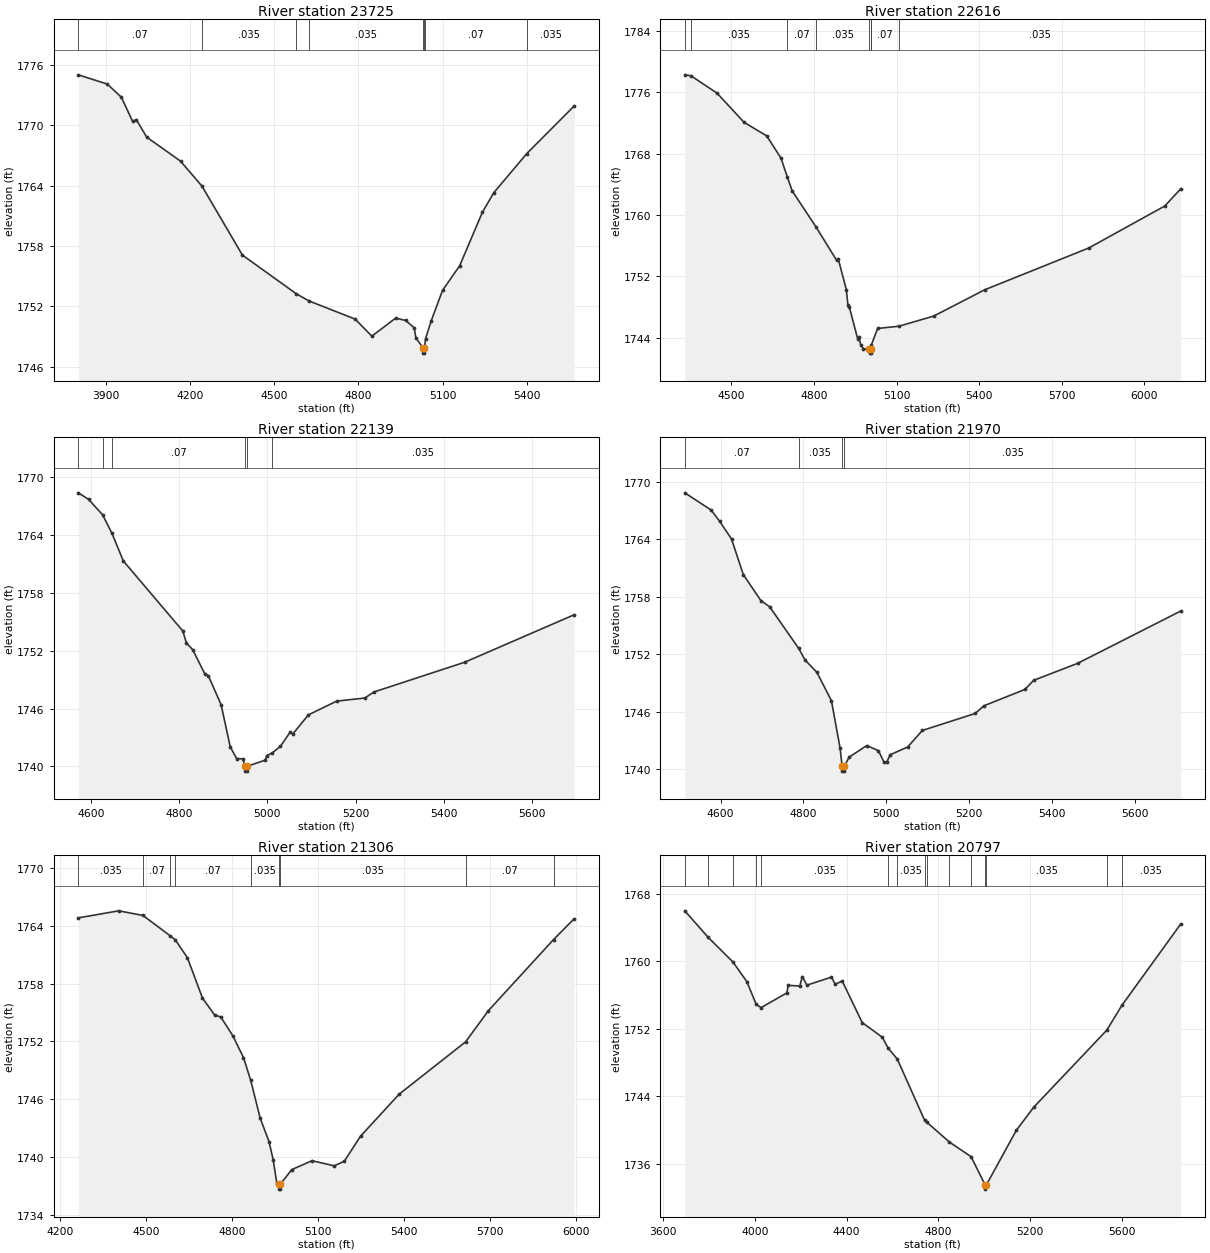
Type RM Length L Ch R = 1,23725,1109,1109,1109
BEGIN DESCRIPTION:
Mapping XS c52b2d95
END DESCRIPTION:
XS GIS Cut Line= 3
      1658574.49      6951995.06      1658665.64      6953195.60
      1658759.38      6953750.24
#Sta/Elev= 30
  3802.2 1775.01  3905.4 1774.09  3955.6 1772.78  3995.7 1770.37  4008.9 1770.55
  4045.8 1768.81  4166.2 1766.43  4242.7 1763.94  4386.8 1757.08  4577.9 1753.25
  4623.9 1752.52  4788.0 1750.72  4848.1 1749.02  4932.6 1750.81  4968.5 1750.58
  4998.6 1749.85  5004.9 1748.85  5030.8 1747.83  5031.2 1747.33  5035.2 1747.33
  5035.5 1747.83  5036.0 1747.96  5039.1 1748.75  5059.3 1750.53  5099.9 1753.58
  5160.8 1756.02  5241.9 1761.35  5282.5 1763.29  5400.0 1767.18  5568.7 1771.91
#Mann=8,-1,0
  3802.2    0.07       0  4242.7   0.035       0  4577.9    0.07       0
  4623.9   0.035       0  5030.8   0.035       0  5035.5   0.035       0
  5036.0    0.07       0  5400.0   0.035       0
Bank Sta=5030.8,5035.5
Exp/Cntr=0.3,0.1

Type RM Length L Ch R = 1,22616,477,477,477
BEGIN DESCRIPTION:
Mapping XS 7a24b5fc
END DESCRIPTION:
XS GIS Cut Line= 3
      1657720.32      6951989.85      1657889.60      6952638.31
      1658128.95      6953744.01
#Sta/Elev= 30
  4330.6 1778.29  4352.8 1778.17  4447.8 1775.90  4545.7 1772.10  4628.4 1770.32
  4680.1 1767.42  4703.4 1764.93  4720.7 1763.15  4807.4 1758.44  4882.6 1754.07
  4887.8 1754.32  4917.8 1750.23  4923.1 1748.30  4928.2 1748.03  4958.4 1743.88
  4963.5 1744.14  4969.5 1743.05  4979.8 1742.54  5001.5 1742.48  5001.9 1741.98
  5006.3 1741.98  5006.7 1742.48  5008.9 1743.09  5031.2 1745.20  5108.5 1745.49
  5234.9 1746.81  5420.0 1750.24  5798.5 1755.70  6074.8 1761.18  6132.1 1763.41
#Mann=8,-1,0
  4330.6    0.07       0  4352.8   0.035       0  4703.4    0.07       0
  4807.4   0.035       0  5001.5   0.035       0  5006.7   0.035       0
  5008.9    0.07       0  5108.5   0.035       0
Bank Sta=5001.5,5006.7
Exp/Cntr=0.3,0.1

Type RM Length L Ch R = 1,22139,169,169,169
BEGIN DESCRIPTION:
Mapping XS 2b6cda39
END DESCRIPTION:
XS GIS Cut Line= 3
      1657286.75      6952593.28      1657550.62      6952930.06
      1658020.11      6953442.86
#Sta/Elev= 30
  4571.8 1768.37  4595.1 1767.69  4626.6 1766.10  4648.0 1764.17  4673.7 1761.31
  4808.4 1754.05  4816.5 1752.82  4831.0 1752.10  4858.2 1749.61  4866.3 1749.41
  4895.2 1746.41  4916.0 1742.02  4930.5 1740.82  4944.9 1740.79  4948.7 1740.02
  4949.1 1739.52  4953.5 1739.52  4953.9 1740.02  4994.7 1740.65  4999.1 1741.13
  5011.1 1741.41  5029.5 1742.09  5051.1 1743.53  5057.9 1743.39  5093.1 1745.36
  5157.2 1746.78  5220.7 1747.10  5241.7 1747.73  5447.0 1750.81  5694.9 1755.73
#Mann=6,-1,0
  4571.8    0.07       0  4626.6   0.035       0  4648.0    0.07       0
  4948.7    0.07       0  4953.9    0.07       0  5011.1   0.035       0
Bank Sta=4948.7,4953.9
Exp/Cntr=0.3,0.1

Type RM Length L Ch R = 1,21970,664,664,664
BEGIN DESCRIPTION:
Mapping XS ca80886e
END DESCRIPTION:
XS GIS Cut Line= 3
      1657128.72      6952674.82      1657448.19      6953042.91
      1657963.79      6953530.73
#Sta/Elev= 30
  4513.5 1768.85  4576.9 1767.06  4597.8 1765.87  4626.3 1764.03  4654.8 1760.31
  4697.5 1757.58  4718.4 1756.95  4788.5 1752.61  4803.9 1751.39  4832.4 1750.11
  4867.5 1747.15  4888.5 1742.19  4893.4 1740.29  4893.8 1739.79  4898.2 1739.79
  4898.6 1740.29  4910.2 1741.25  4953.0 1742.46  4981.2 1741.92  4994.6 1740.71
  5000.9 1740.71  5009.5 1741.50  5051.6 1742.31  5087.2 1744.04  5214.6 1745.81
  5235.6 1746.61  5334.7 1748.32  5355.8 1749.27  5462.2 1751.05  5710.7 1756.50
#Mann=4,-1,0
  4513.5    0.07       0  4788.5   0.035       0  4893.4   0.035       0
  4898.6   0.035       0
Bank Sta=4893.4,4898.6
Exp/Cntr=0.3,0.1

Type RM Length L Ch R = 1,21306,509,509,509
BEGIN DESCRIPTION:
Mapping XS e94d7363
END DESCRIPTION:
XS GIS Cut Line= 3
      1656551.99      6952727.60      1656937.43      6953359.57
      1657662.99      6954033.06
#Sta/Elev= 30
  4262.7 1764.82  4403.7 1765.55  4488.3 1765.07  4583.5 1762.95  4601.0 1762.54
  4643.4 1760.68  4695.6 1756.51  4738.3 1754.73  4759.6 1754.54  4802.2 1752.56
  4839.0 1750.32  4864.2 1747.96  4897.1 1744.04  4928.0 1741.60  4942.5 1739.73
  4955.2 1737.30  4962.1 1737.16  4962.5 1736.66  4967.0 1736.66  4967.4 1737.16
  5007.2 1738.68  5078.1 1739.61  5155.7 1739.08  5190.9 1739.56  5247.6 1742.16
  5382.0 1746.51  5614.1 1751.95  5693.7 1755.19  5921.1 1762.57  5992.9 1764.73
#Mann=9,-1,0
  4262.7   0.035       0  4488.3    0.07       0  4583.5   0.035       0
  4601.0    0.07       0  4864.2   0.035       0  4962.1   0.035       0
  4967.4   0.035       0  5614.1    0.07       0  5921.1   0.035       0
Bank Sta=4962.1,4967.4
Exp/Cntr=0.3,0.1

Type RM Length L Ch R = 1,20797,612,612,612
BEGIN DESCRIPTION:
Mapping XS 51de6a43
END DESCRIPTION:
XS GIS Cut Line= 3
      1656170.07      6952505.42      1656607.57      6953734.57
      1656996.47      6954498.49
#Sta/Elev= 30
  3694.5 1766.01  3795.8 1762.88  3904.6 1759.93  3965.3 1757.60  4005.5 1754.92
  4026.9 1754.52  4139.7 1756.27  4145.0 1757.17  4196.0 1757.08  4206.7 1758.21
  4226.9 1757.19  4334.1 1758.14  4350.2 1757.30  4381.0 1757.67  4468.2 1752.74
  4555.4 1751.02  4581.4 1749.70  4620.8 1748.43  4739.9 1741.17  4750.6 1740.90
  4848.2 1738.57  4942.8 1736.83  5003.9 1733.48  5004.3 1732.98  5009.4 1733.48
  5140.1 1739.96  5216.2 1742.71  5534.3 1751.84  5600.5 1754.80  5856.4 1764.43
#Mann=15,-1,0
  3694.5   0.035       0  3795.8    0.07       0  3904.6   0.035       0
  4005.5    0.07       0  4026.9   0.035       0  4581.4    0.07       0
  4620.8   0.035       0  4739.9    0.07       0  4750.6   0.035       0
  4848.2    0.07       0  4942.8   0.035       0  5003.9   0.035       0
  5009.4   0.035       0  5534.3    0.07       0  5600.5   0.035       0
Bank Sta=5003.9,5009.4
Exp/Cntr=0.3,0.1

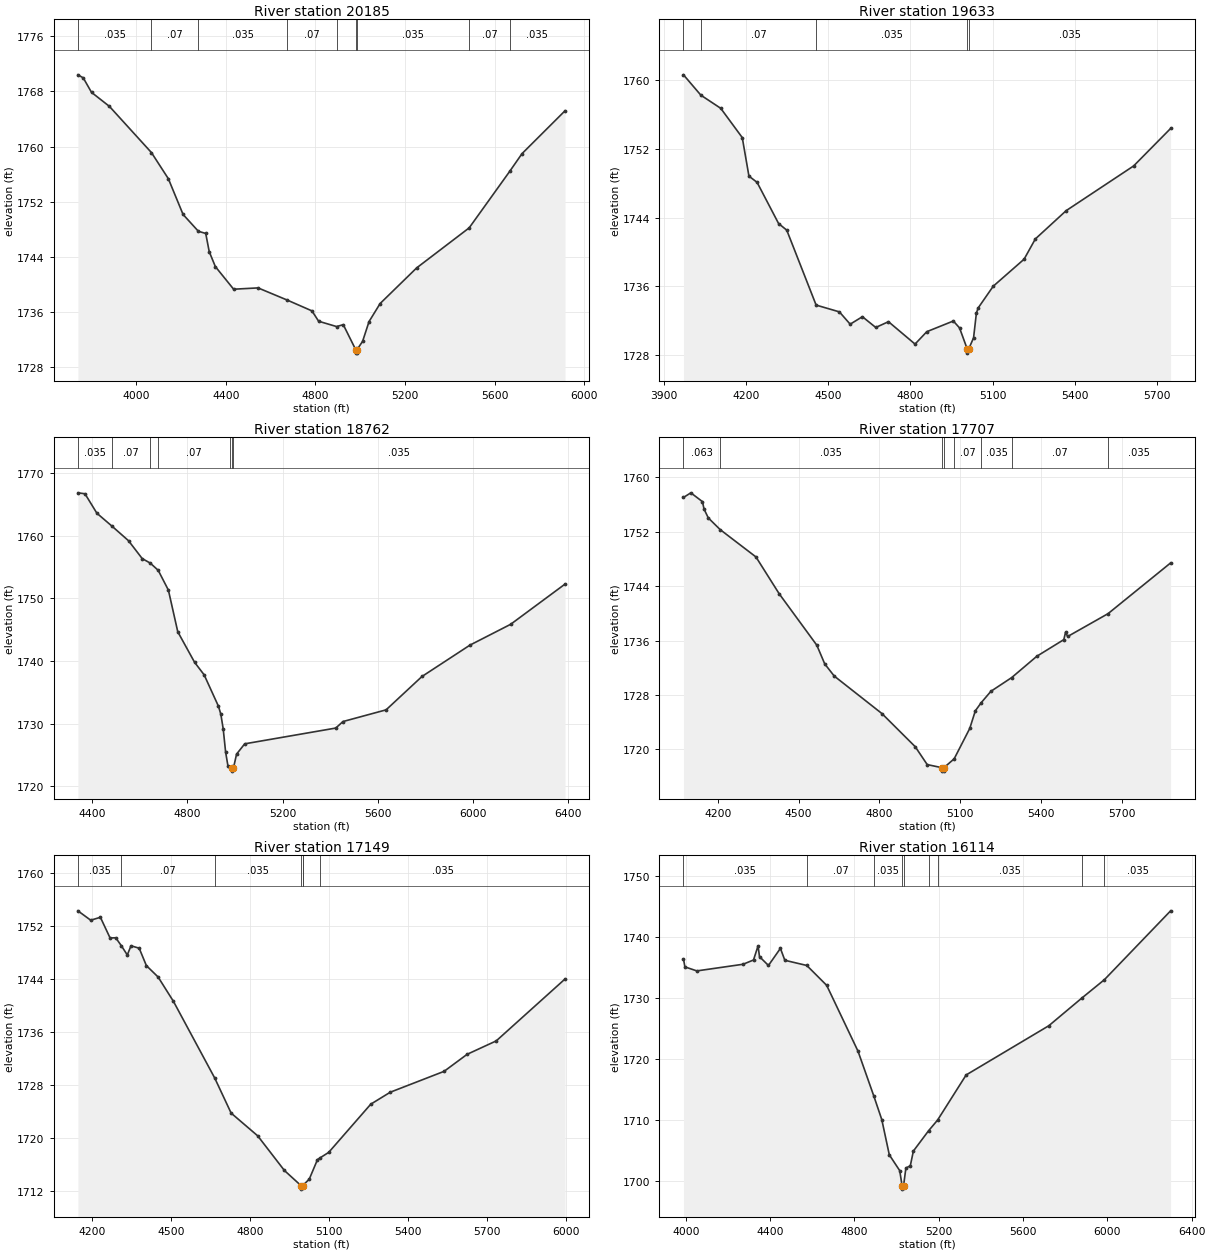
Type RM Length L Ch R = 1,20185,552,552,552
BEGIN DESCRIPTION:
Mapping XS 0771f87c
END DESCRIPTION:
XS GIS Cut Line= 3
      1655458.26      6952911.66      1656104.09      6953991.52
      1656680.13      6954702.89
#Sta/Elev= 30
  3740.3 1770.39  3764.2 1769.95  3801.1 1767.85  3880.9 1765.82  4068.6 1759.12
  4143.9 1755.34  4209.6 1750.16  4278.0 1747.72  4310.7 1747.41  4326.3 1744.77
  4353.6 1742.61  4435.2 1739.33  4544.2 1739.52  4674.1 1737.76  4784.7 1736.19
  4814.5 1734.69  4894.5 1733.92  4924.5 1734.19  4979.9 1730.57  4980.4 1730.07
  4985.2 1730.07  4985.6 1730.57  5010.6 1731.77  5039.4 1734.64  5089.0 1737.26
  5252.0 1742.42  5486.3 1748.22  5667.2 1756.41  5722.0 1758.97  5913.9 1765.18
#Mann=9,-1,0
  3740.3   0.035       0  4068.6    0.07       0  4278.0   0.035       0
  4674.1    0.07       0  4894.5   0.035       0  4979.9   0.035       0
  4985.6   0.035       0  5486.3    0.07       0  5667.2   0.035       0
Bank Sta=4979.9,4985.6
Exp/Cntr=0.3,0.1

Type RM Length L Ch R = 1,19633,871,871,871
BEGIN DESCRIPTION:
Mapping XS a6504fb7
END DESCRIPTION:
XS GIS Cut Line= 3
      1655221.70      6953182.52      1655600.16      6954140.82
      1655759.88      6954870.01
#Sta/Elev= 30
  3972.6 1760.58  4035.9 1758.22  4108.5 1756.69  4187.0 1753.29  4211.3 1748.82
  4241.1 1748.09  4319.5 1743.31  4349.3 1742.54  4456.4 1733.84  4541.3 1733.05
  4580.6 1731.62  4625.2 1732.49  4673.9 1731.24  4720.3 1731.91  4817.2 1729.31
  4860.1 1730.75  4956.9 1731.99  4979.5 1731.19  5007.3 1728.76  5007.8 1728.26
  5013.2 1728.76  5030.7 1730.04  5041.0 1732.91  5047.5 1733.51  5102.4 1736.03
  5215.0 1739.17  5256.0 1741.52  5368.6 1744.81  5614.6 1750.00  5749.4 1754.35
#Mann=5,-1,0
  3972.6   0.035       0  4035.9    0.07       0  4456.4   0.035       0
  5007.3   0.035       0  5013.2   0.035       0
Bank Sta=5007.3,5013.2
Exp/Cntr=0.3,0.1

Type RM Length L Ch R = 1,18762,1055,1055,1055
BEGIN DESCRIPTION:
Mapping XS cb239bb5
END DESCRIPTION:
XS GIS Cut Line= 3
      1654850.16      6953078.30      1654881.41      6953744.99
      1655037.45      6955114.71
#Sta/Elev= 30
  4340.0 1766.87  4369.7 1766.72  4419.8 1763.61  4481.8 1761.59  4552.6 1759.22
  4610.0 1756.37  4644.0 1755.64  4677.3 1754.49  4720.1 1751.33  4759.5 1744.67
  4830.2 1739.79  4870.3 1737.79  4930.3 1732.78  4940.4 1731.50  4950.4 1729.14
  4960.4 1725.47  4970.4 1723.20  4979.4 1723.14  4987.4 1722.91  4987.9 1722.41
  4993.4 1722.91  5006.4 1725.12  5040.6 1726.77  5423.1 1729.29  5453.3 1730.33
  5634.5 1732.20  5785.2 1737.53  5986.7 1742.54  6157.8 1745.87  6386.0 1752.29
#Mann=7,-1,0
  4340.0   0.035       0  4481.8    0.07       0  4644.0   0.035       0
  4677.3    0.07       0  4979.4   0.035       0  4987.4   0.035       0
  4993.4   0.035       0
Bank Sta=4987.4,4993.4
Exp/Cntr=0.3,0.1

Type RM Length L Ch R = 1,17707,558,558,558
BEGIN DESCRIPTION:
Mapping XS a49101cc
END DESCRIPTION:
XS GIS Cut Line= 3
      1653834.19      6953693.15      1654295.99      6954498.69
      1654844.61      6955186.21
#Sta/Elev= 30
  4072.7 1757.04  4100.0 1757.72  4143.2 1756.42  4149.0 1755.33  4164.8 1754.03
  4208.9 1752.31  4341.7 1748.29  4428.0 1742.87  4567.6 1735.31  4597.0 1732.56
  4632.3 1730.77  4809.2 1725.26  4932.9 1720.38  4977.4 1717.75  5032.9 1717.29
  5033.4 1716.79  5038.6 1716.79  5039.1 1717.29  5077.4 1718.60  5135.3 1723.07
  5156.1 1725.67  5178.3 1726.88  5213.8 1728.53  5291.0 1730.55  5384.1 1733.68
  5484.4 1736.13  5490.8 1737.20  5498.8 1736.59  5648.6 1739.95  5880.8 1747.41
#Mann=8,-1,0
  4072.7   0.063       0  4208.9   0.035       0  5032.9   0.035       0
  5039.1   0.035       0  5077.4    0.07       0  5178.3   0.035       0
  5291.0    0.07       0  5648.6   0.035       0
Bank Sta=5032.9,5039.1
Exp/Cntr=0.3,0.1

Type RM Length L Ch R = 1,17149,1035,1035,1035
BEGIN DESCRIPTION:
Mapping XS c34f8adc
END DESCRIPTION:
XS GIS Cut Line= 3
      1653407.08      6954057.69      1653851.55      6954790.36
      1654360.53      6955642.13
#Sta/Elev= 30
  4145.5 1754.34  4194.1 1752.92  4230.9 1753.36  4267.7 1750.23  4289.1 1750.26
  4310.4 1749.06  4333.0 1747.66  4347.2 1749.05  4378.2 1748.68  4405.4 1746.05
  4450.0 1744.32  4508.4 1740.62  4665.0 1729.02  4727.2 1723.72  4828.0 1720.28
  4929.5 1715.03  4993.4 1712.71  4993.9 1712.21  4999.8 1712.71  5000.4 1712.80
  5023.9 1713.73  5055.0 1716.68  5065.5 1716.96  5097.8 1717.78  5257.3 1725.07
  5331.3 1726.88  5535.6 1730.04  5623.1 1732.62  5733.6 1734.65  5994.7 1744.02
#Mann=7,-1,0
  4145.5   0.035       0  4310.4    0.07       0  4665.0   0.035       0
  4993.4   0.035       0  4999.8   0.035       0  5000.4    0.07       0
  5065.5   0.035       0
Bank Sta=4993.4,4999.8
Exp/Cntr=0.3,0.1

Type RM Length L Ch R = 1,16114,955,955,955
BEGIN DESCRIPTION:
Mapping XS cbb01e2b
END DESCRIPTION:
XS GIS Cut Line= 3
      1652361.05      6954712.13      1653104.09      6955392.67
      1654151.36      6956169.45
#Sta/Elev= 30
  3988.6 1736.40  3995.3 1735.10  4052.0 1734.44  4271.6 1735.53  4320.9 1736.23
  4342.5 1738.54  4349.3 1736.77  4391.8 1735.33  4448.6 1738.13  4469.5 1736.18
  4573.7 1735.33  4668.1 1732.08  4816.7 1721.31  4892.1 1713.94  4929.6 1710.11
  4965.3 1704.35  5014.8 1701.76  5026.1 1699.24  5026.6 1698.74  5032.7 1699.24
  5044.0 1702.19  5064.9 1702.56  5079.5 1704.97  5151.6 1708.29  5194.4 1710.04
  5329.9 1717.42  5722.1 1725.47  5879.6 1730.02  5986.1 1733.01  6300.1 1744.27
#Mann=9,-1,0
  3988.6   0.035       0  4573.7    0.07       0  4892.1   0.035       0
  5026.1   0.035       0  5032.7   0.035       0  5151.6    0.07       0
  5194.4   0.035       0  5879.6    0.07       0  5986.1   0.035       0
Bank Sta=5026.1,5032.7
Exp/Cntr=0.3,0.1

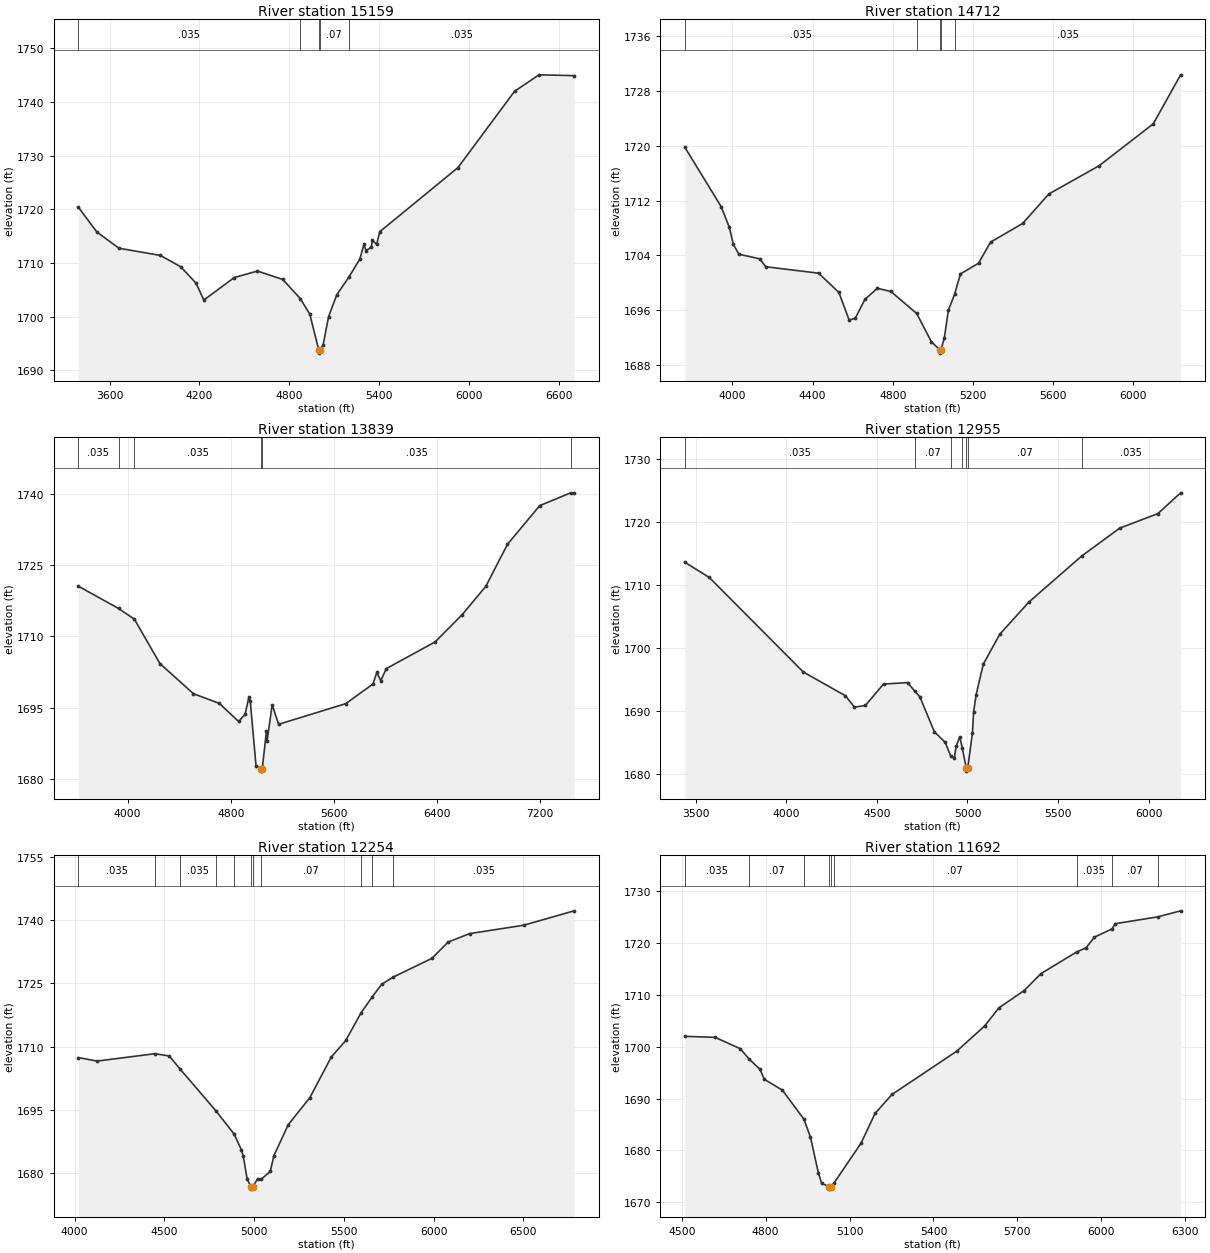
Type RM Length L Ch R = 1,15159,447,447,447
BEGIN DESCRIPTION:
Mapping XS 9c391326
END DESCRIPTION:
XS GIS Cut Line= 3
      1651195.58      6955823.24      1652751.08      6956239.90
      1654414.32      6956597.55
#Sta/Elev= 30
  3391.5 1720.42  3515.1 1715.79  3663.2 1712.76  3939.6 1711.42  4074.2 1709.33
  4177.7 1706.26  4229.5 1703.10  4432.7 1707.30  4587.7 1708.51  4757.4 1706.94
  4874.3 1703.37  4937.6 1700.48  4997.9 1693.72  4998.4 1693.22  5004.6 1693.72
  5026.3 1694.73  5063.1 1700.04  5118.4 1704.12  5197.6 1707.34  5271.8 1710.76
  5299.7 1713.53  5312.7 1712.33  5349.0 1712.95  5354.2 1714.23  5384.3 1713.49
  5404.8 1715.84  5926.4 1727.77  6305.5 1742.02  6468.5 1745.07  6703.1 1744.92
#Mann=5,-1,0
  3391.5   0.035       0  4874.3    0.07       0  4997.9    0.07       0
  5004.6    0.07       0  5197.6   0.035       0
Bank Sta=4997.9,5004.6
Exp/Cntr=0.3,0.1

Type RM Length L Ch R = 1,14712,873,873,873
BEGIN DESCRIPTION:
Mapping XS 9f14933a
END DESCRIPTION:
XS GIS Cut Line= 3
      1651245.81      6956379.85      1652461.14      6956575.17
      1653701.26      6956653.22
#Sta/Elev= 30
  3762.6 1719.82  3944.1 1711.13  3984.6 1708.13  4004.9 1705.61  4032.4 1704.18
  4136.5 1703.51  4166.9 1702.35  4430.2 1701.41  4531.5 1698.59  4582.2 1694.58
  4612.6 1694.81  4661.4 1697.59  4723.3 1699.20  4790.3 1698.74  4919.4 1695.53
  4992.9 1691.38  5034.1 1690.23  5034.6 1689.73  5040.8 1690.23  5057.5 1691.98
  5077.5 1696.00  5108.9 1698.36  5137.7 1701.30  5227.8 1702.86  5288.0 1705.95
  5448.3 1708.68  5578.5 1712.98  5829.0 1717.10  6099.6 1723.23  6236.1 1730.39
#Mann=5,-1,0
  3762.6   0.035       0  4919.4    0.07       0  5034.1    0.07       0
  5040.8    0.07       0  5108.9   0.035       0
Bank Sta=5034.1,5040.8
Exp/Cntr=0.3,0.1

Type RM Length L Ch R = 1,13839,884,884,884
BEGIN DESCRIPTION:
Mapping XS cbaad80e
END DESCRIPTION:
XS GIS Cut Line= 3
      1650372.56      6956962.12      1651751.08      6956948.23
      1654211.42      6956788.60
#Sta/Elev= 30
  3618.1 1720.56  3929.7 1715.86  4052.6 1713.62  4250.6 1704.28  4510.6 1697.94
  4710.6 1695.91  4860.6 1692.11  4910.6 1693.58  4940.6 1697.26  4950.6 1696.50
  4996.1 1682.70  5037.2 1682.16  5037.7 1681.66  5044.2 1682.16  5076.6 1690.11
  5081.6 1688.00  5120.9 1695.61  5171.0 1691.51  5691.2 1695.85  5902.5 1699.98
  5932.6 1702.43  5962.6 1700.67  6006.0 1703.22  6383.5 1708.82  6594.0 1714.56
  6777.9 1720.54  6944.7 1729.34  7195.2 1737.49  7435.4 1740.18  7462.2 1740.18
#Mann=6,-1,0
  3618.1   0.035       0  3929.7    0.07       0  4052.6   0.035       0
  5037.2   0.035       0  5044.2   0.035       0  7435.4    0.07       0
Bank Sta=5037.2,5044.2
Exp/Cntr=0.3,0.1

Type RM Length L Ch R = 1,12955,701,701,701
BEGIN DESCRIPTION:
Mapping XS d6e264b8
END DESCRIPTION:
XS GIS Cut Line= 3
      1650790.09      6957408.50      1652356.97      6957490.97
      1653520.05      6957582.10
#Sta/Elev= 30
  3440.4 1713.65  3575.5 1711.23  4094.0 1696.22  4326.5 1692.44  4376.6 1690.63
  4436.7 1690.90  4536.8 1694.30  4669.8 1694.53  4708.3 1693.21  4737.1 1692.29
  4817.2 1686.73  4877.3 1685.03  4906.4 1682.95  4927.4 1682.54  4937.4 1684.42
  4957.4 1685.93  4971.6 1684.13  4993.4 1680.97  4993.9 1680.47  5001.5 1680.97
  5027.5 1686.57  5034.0 1689.83  5047.6 1692.59  5087.7 1697.48  5178.0 1702.20
  5338.5 1707.31  5629.6 1714.62  5840.0 1719.06  6050.7 1721.37  6176.1 1724.67
#Mann=7,-1,0
  3440.4   0.035       0  4708.3    0.07       0  4906.4   0.035       0
  4971.6    0.07       0  4993.4    0.07       0  5001.5    0.07       0
  5629.6   0.035       0
Bank Sta=4993.4,5001.5
Exp/Cntr=0.3,0.1

Type RM Length L Ch R = 1,12254,562,562,562
BEGIN DESCRIPTION:
Mapping XS f18ff1b6
END DESCRIPTION:
XS GIS Cut Line= 3
      1650981.55      6957922.33      1651945.09      6958026.50
      1653736.78      6958078.58
#Sta/Elev= 30
  4021.1 1707.43  4125.3 1706.60  4448.5 1708.35  4527.5 1707.80  4589.8 1704.62
  4788.4 1694.74  4887.8 1689.34  4929.8 1685.53  4939.9 1684.04  4961.4 1678.61
  4983.6 1676.73  4984.1 1676.23  4991.7 1676.73  5020.2 1678.69  5039.2 1678.56
  5090.2 1680.43  5110.2 1684.15  5190.2 1691.51  5310.3 1697.91  5430.3 1707.58
  5510.4 1711.48  5595.1 1717.99  5656.0 1721.71  5710.5 1724.80  5775.5 1726.53
  5990.6 1730.96  6080.6 1734.82  6200.7 1736.83  6500.8 1738.81  6782.7 1742.23
#Mann=11,-1,0
  4021.1   0.035       0  4448.5    0.07       0  4589.8   0.035       0
  4788.4    0.07       0  4887.8   0.035       0  4983.6   0.035       0
  4991.7   0.035       0  5039.2    0.07       0  5595.1   0.035       0
  5656.0    0.07       0  5775.5   0.035       0
Bank Sta=4983.6,4991.7
Exp/Cntr=0.3,0.1

Type RM Length L Ch R = 1,11692,750,750,750
BEGIN DESCRIPTION:
Mapping XS 51eda9b2
END DESCRIPTION:
XS GIS Cut Line= 3
      1651366.96      6958521.29      1651846.14      6958557.75
      1653131.32      6958417.26
#Sta/Elev= 30
  4510.7 1701.99  4619.1 1701.80  4709.3 1699.61  4740.5 1697.63  4779.5 1695.63
  4795.7 1693.69  4859.7 1691.62  4936.6 1686.05  4960.0 1682.60  4988.2 1675.74
  5000.2 1673.65  5026.0 1673.04  5026.5 1672.54  5034.2 1673.04  5044.1 1673.69
  5141.0 1681.39  5191.3 1687.14  5251.7 1690.79  5483.0 1699.12  5582.9 1703.98
  5633.9 1707.47  5724.5 1710.82  5784.8 1714.10  5912.2 1718.26  5945.8 1719.06
  5976.0 1721.12  6039.4 1722.72  6049.3 1723.70  6202.4 1725.03  6284.1 1726.19
#Mann=9,-1,0
  4510.7   0.035       0  4740.5    0.07       0  4936.6   0.035       0
  5026.0   0.035       0  5034.2   0.035       0  5044.1    0.07       0
  5912.2   0.035       0  6039.4    0.07       0  6202.4   0.035       0
Bank Sta=5026,5034.2
Exp/Cntr=0.3,0.1

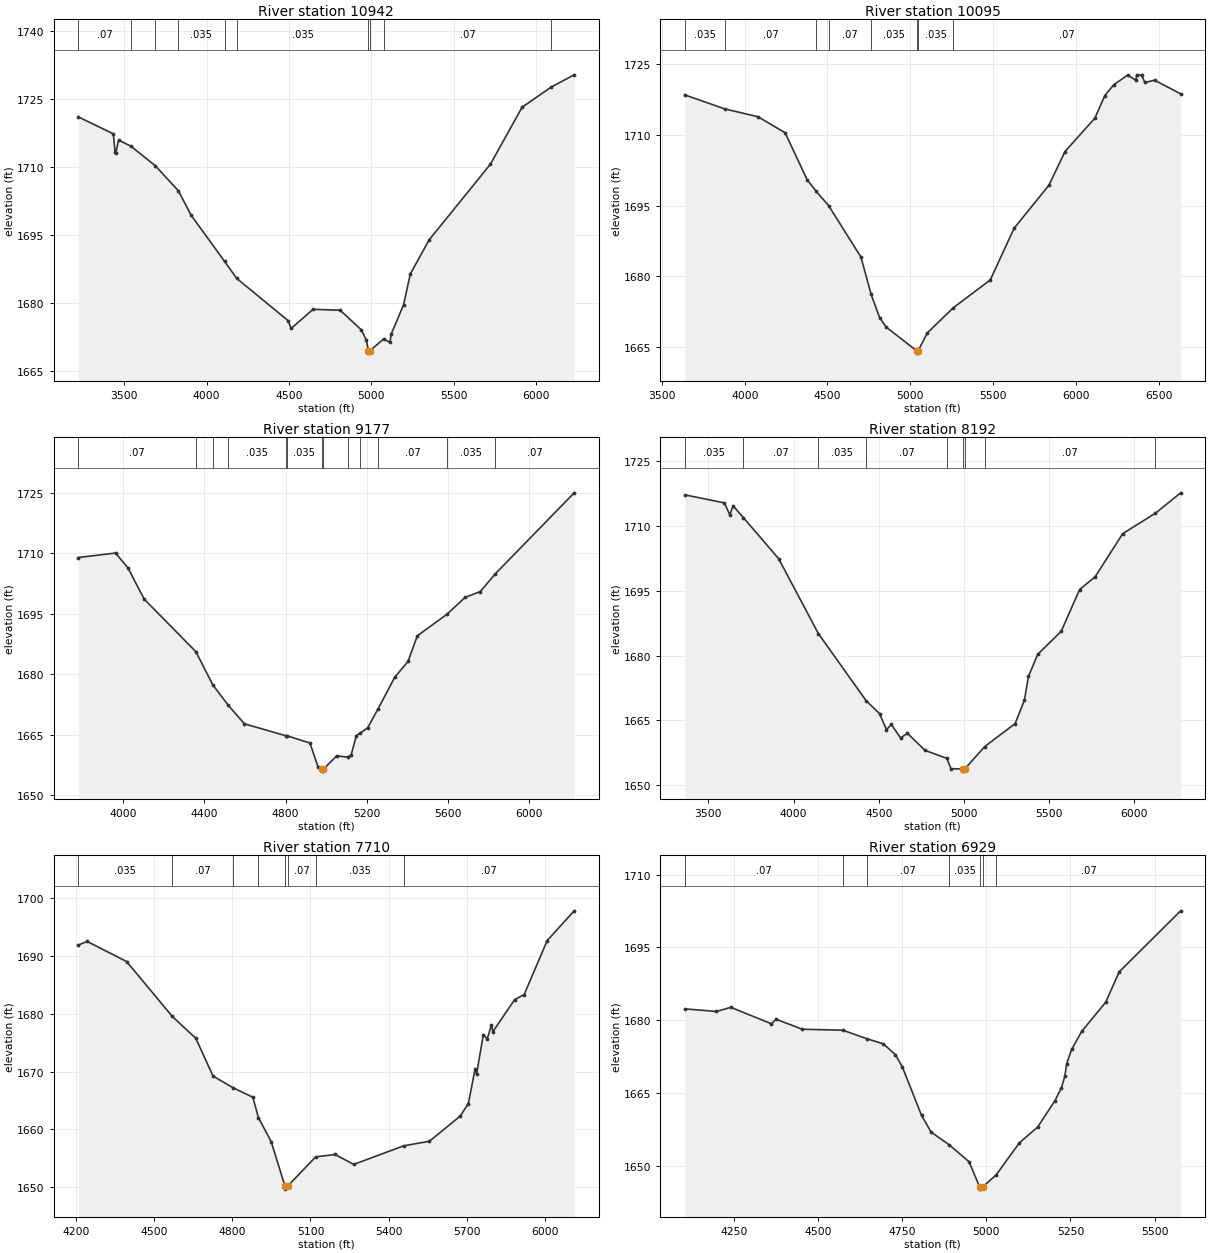
Type RM Length L Ch R = 1,10942,847,847,847
BEGIN DESCRIPTION:
Mapping XS 2d509e9f
END DESCRIPTION:
XS GIS Cut Line= 3
      1650262.79      6959823.38      1651945.09      6959276.50
      1653148.21      6958964.00
#Sta/Elev= 30
  3220.8 1720.97  3433.4 1717.24  3443.6 1713.28  3448.8 1713.03  3465.0 1715.86
  3540.0 1714.52  3688.5 1710.20  3828.0 1704.71  3906.6 1699.26  4108.8 1689.13
  4182.3 1685.38  4495.5 1676.03  4513.6 1674.32  4646.6 1678.54  4811.6 1678.34
  4939.4 1674.03  4971.3 1671.70  4982.9 1669.38  4983.4 1668.88  4991.3 1669.38
  5075.4 1672.01  5113.6 1671.24  5120.9 1673.04  5196.3 1679.51  5237.4 1686.32
  5351.3 1693.83  5724.0 1710.54  5916.5 1723.10  6092.7 1727.54  6232.8 1730.25
#Mann=10,-1,0
  3220.8    0.07       0  3540.0   0.035       0  3688.5    0.07       0
  3828.0   0.035       0  4108.8    0.07       0  4182.3   0.035       0
  4982.9   0.035       0  4991.3   0.035       0  5075.4    0.07       0
  6092.7   0.035       0
Bank Sta=4982.9,4991.3
Exp/Cntr=0.3,0.1

Type RM Length L Ch R = 1,10095,918,918,918
BEGIN DESCRIPTION:
Mapping XS fb9fd28b
END DESCRIPTION:
XS GIS Cut Line= 3
      1650621.09      6960393.50      1651933.55      6960129.62
      1653475.17      6959525.47
#Sta/Elev= 30
  3638.3 1718.52  3879.5 1715.55  4080.9 1713.88  4244.1 1710.49  4376.7 1700.54
  4432.4 1698.04  4506.5 1695.04  4702.1 1684.11  4763.6 1676.19  4815.3 1671.22
  4854.7 1669.24  5038.5 1664.22  5039.0 1663.72  5047.5 1664.22  5103.4 1668.02
  5259.7 1673.34  5483.3 1679.26  5627.0 1690.22  5837.8 1699.37  5934.5 1706.50
  6115.3 1713.60  6174.9 1718.38  6229.2 1720.67  6313.2 1722.73  6362.1 1721.61
  6367.5 1722.78  6397.3 1722.72  6416.4 1721.16  6476.0 1721.63  6632.8 1718.75
#Mann=8,-1,0
  3638.3   0.035       0  3879.5    0.07       0  4432.4   0.035       0
  4506.5    0.07       0  4763.6   0.035       0  5038.5   0.035       0
  5047.5   0.035       0  5259.7    0.07       0
Bank Sta=5038.5,5047.5
Exp/Cntr=0.3,0.1

Type RM Length L Ch R = 1,9177,985,985,985
BEGIN DESCRIPTION:
Mapping XS b527496f
END DESCRIPTION:
XS GIS Cut Line= 3
      1651093.25      6960768.51      1652294.66      6960914.35
      1653501.46      6960671.60
#Sta/Elev= 30
  3779.1 1708.93  3962.2 1710.04  4022.6 1706.42  4103.2 1698.64  4358.2 1685.58
  4441.0 1677.41  4517.6 1672.31  4596.8 1667.75  4799.7 1664.81  4806.8 1664.78
  4919.2 1663.00  4959.5 1657.03  4976.7 1656.53  4977.2 1656.03  4986.1 1656.53
  5051.4 1659.83  5105.2 1659.49  5122.3 1660.04  5148.0 1664.83  5165.7 1665.39
  5204.0 1666.79  5253.8 1671.35  5336.5 1679.24  5402.3 1683.19  5448.1 1689.54
  5593.9 1694.87  5683.3 1699.05  5758.3 1700.51  5831.5 1704.86  6220.3 1724.95
#Mann=13,-1,0
  3779.1    0.07       0  4358.2   0.035       0  4441.0    0.07       0
  4517.6   0.035       0  4799.7    0.07       0  4806.8   0.035       0
  4976.7   0.035       0  4986.1   0.035       0  5105.2    0.07       0
  5165.7   0.035       0  5253.8    0.07       0  5593.9   0.035       0
  5831.5    0.07       0
Bank Sta=4976.7,4986.1
Exp/Cntr=0.3,0.1

Type RM Length L Ch R = 1,8192,482,482,482
BEGIN DESCRIPTION:
Mapping XS 8b9f91a9
END DESCRIPTION:
XS GIS Cut Line= 3
      1650287.69      6961358.79      1651877.99      6961699.07
      1653071.22      6962170.81
#Sta/Elev= 30
  3361.4 1717.25  3593.9 1715.39  3625.1 1712.64  3645.0 1714.70  3704.8 1711.99
  3911.6 1702.50  4145.9 1685.08  4425.2 1669.59  4504.0 1666.59  4544.9 1662.87
  4573.4 1664.08  4628.0 1660.93  4667.2 1662.05  4771.3 1658.07  4899.0 1656.23
  4923.3 1653.84  4994.7 1653.77  4995.2 1653.27  5004.3 1653.77  5121.1 1658.95
  5299.6 1664.28  5353.7 1669.64  5378.1 1675.20  5432.2 1680.31  5570.1 1685.66
  5678.2 1695.33  5769.5 1698.29  5930.8 1708.26  6123.0 1713.00  6270.8 1717.72
#Mann=9,-1,0
  3361.4   0.035       0  3704.8    0.07       0  4145.9   0.035       0
  4425.2    0.07       0  4899.0   0.035       0  4994.7   0.035       0
  5004.3   0.035       0  5121.1    0.07       0  6123.0   0.035       0
Bank Sta=4994.7,5004.3
Exp/Cntr=0.3,0.1

Type RM Length L Ch R = 1,7710,781,781,781
BEGIN DESCRIPTION:
Mapping XS 87e5bb07
END DESCRIPTION:
XS GIS Cut Line= 4
      1650771.34      6962136.04      1651556.04      6962024.94
      1652010.90      6961917.30      1652620.98      6962125.28
#Sta/Elev= 30
  4208.3 1691.92  4242.3 1692.54  4393.8 1689.06  4568.8 1679.58  4659.7 1675.75
  4725.7 1669.24  4803.2 1667.19  4878.6 1665.57  4900.2 1662.03  4949.3 1657.85
  5002.2 1650.16  5002.7 1649.66  5012.0 1650.16  5119.8 1655.24  5195.0 1655.66
  5265.8 1653.93  5457.3 1657.15  5557.1 1657.95  5675.2 1662.31  5706.6 1664.48
  5732.6 1670.53  5737.9 1669.57  5764.0 1676.42  5779.0 1675.67  5795.3 1678.12
  5800.6 1676.92  5884.1 1682.47  5920.7 1683.34  6009.4 1692.70  6112.8 1697.84
#Mann=8,-1,0
  4208.3   0.035       0  4568.8    0.07       0  4803.2   0.035       0
  4900.2    0.07       0  5002.2    0.07       0  5012.0    0.07       0
  5119.8   0.035       0  5457.3    0.07       0
Bank Sta=5002.2,5012
Exp/Cntr=0.3,0.1

Type RM Length L Ch R = 1,6929,529,529,529
BEGIN DESCRIPTION:
Mapping XS ae2178e1
END DESCRIPTION:
XS GIS Cut Line= 3
      1651469.23      6962865.22      1652128.96      6962267.99
      1652705.36      6962184.66
#Sta/Elev= 30
  4105.0 1682.34  4199.1 1681.80  4241.7 1682.65  4362.0 1679.27  4376.2 1680.19
  4453.9 1678.14  4574.3 1677.94  4646.2 1676.17  4694.5 1675.13  4730.3 1672.89
  4751.3 1670.32  4808.0 1660.38  4836.4 1656.95  4890.7 1654.29  4949.3 1650.82
  4980.1 1645.69  4980.6 1645.19  4990.2 1645.69  5029.7 1648.13  5098.3 1654.72
  5152.6 1657.98  5203.1 1663.29  5223.3 1666.04  5233.4 1668.43  5238.9 1671.03
  5253.6 1673.97  5283.9 1677.72  5354.6 1683.69  5395.1 1689.99  5577.3 1702.54
#Mann=7,-1,0
  4105.0    0.07       0  4574.3   0.035       0  4646.2    0.07       0
  4890.7   0.035       0  4980.1   0.035       0  4990.2   0.035       0
  5029.7    0.07       0
Bank Sta=4980.1,4990.2
Exp/Cntr=0.3,0.1