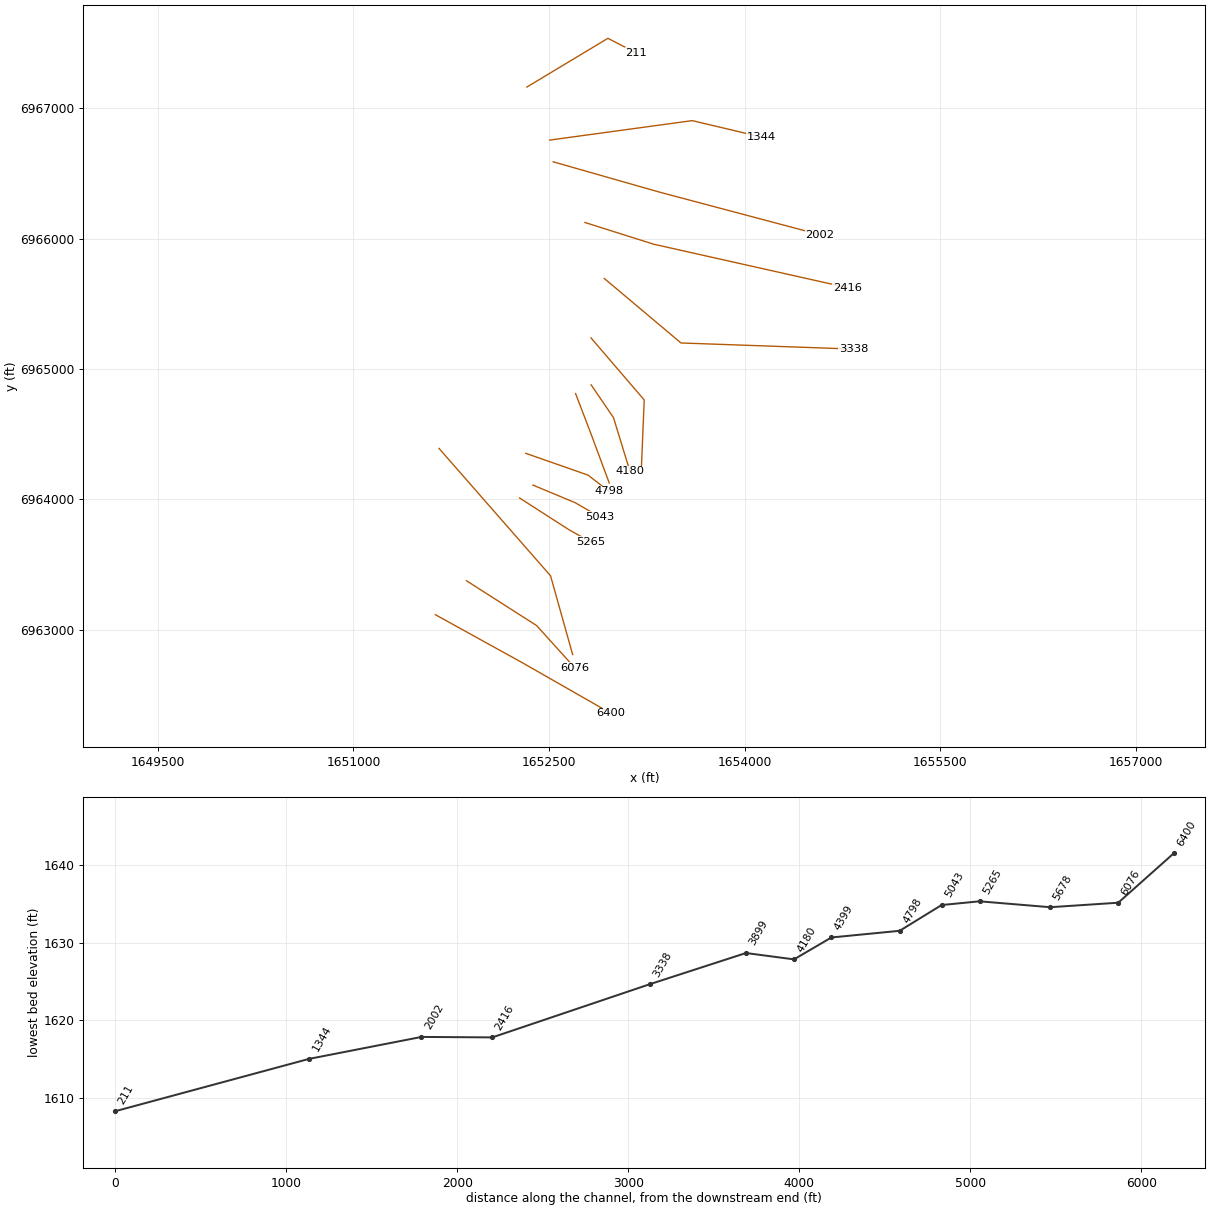
HEC-RAS study Chimney Creek 1142.prj: Chimney Creek 1142 Base Level Engineering

--- Chimney Creek 1142.g01 (geometry) --- (continued)

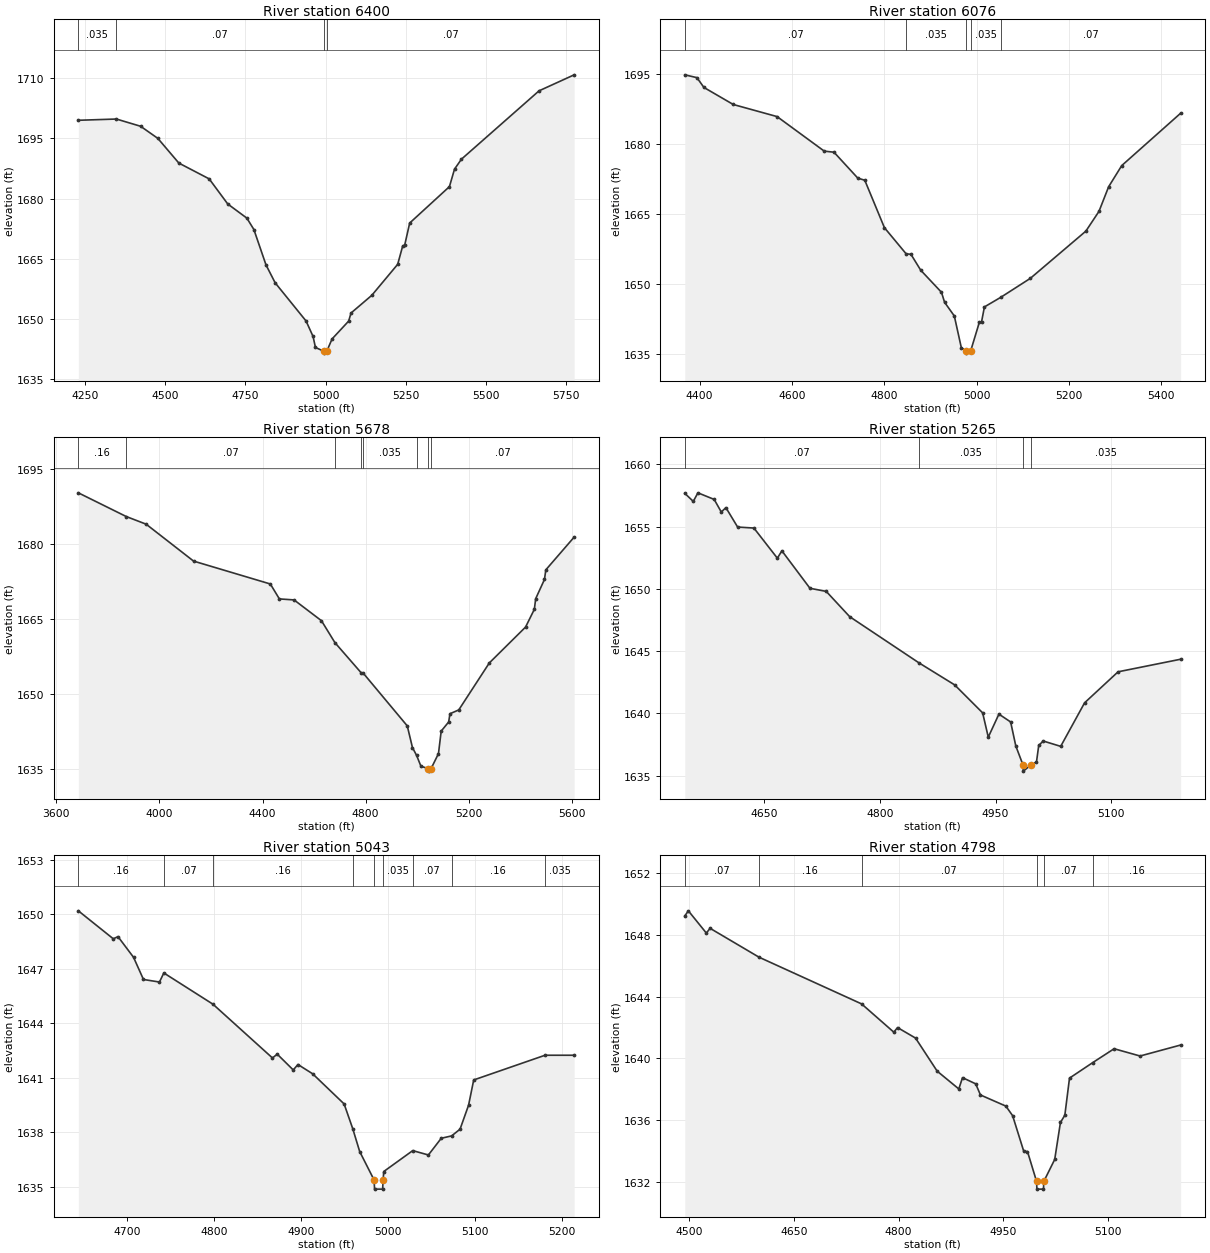
Type RM Length L Ch R = 1,6400,324,324,324
BEGIN DESCRIPTION:
Mapping XS 28da5d27
END DESCRIPTION:
XS GIS Cut Line= 3
      1651628.02      6963115.72      1652294.66      6962747.68
      1652975.20      6962358.80
#Sta/Elev= 30
  4229.6 1699.49  4348.2 1699.80  4423.7 1698.00  4477.5 1694.98  4542.9 1688.84
  4637.4 1684.91  4695.3 1678.66  4754.9 1675.14  4776.7 1672.31  4814.5 1663.50
  4843.0 1659.05  4939.4 1649.54  4961.2 1645.69  4968.6 1642.96  4993.8 1642.05
  4994.3 1641.55  5004.0 1642.05  5020.5 1645.09  5072.1 1649.52  5079.5 1651.53
  5144.3 1655.94  5224.9 1663.65  5240.7 1668.27  5246.5 1668.34  5262.3 1673.92
  5386.2 1682.98  5402.0 1687.33  5423.6 1689.81  5665.5 1706.82  5774.9 1710.80
#Mann=4,-1,0
  4229.6   0.035       0  4348.2    0.07       0  4993.8    0.07       0
  5004.0    0.07       0
Bank Sta=4993.8,5004
Exp/Cntr=0.3,0.1

Type RM Length L Ch R = 1,6076,398,398,398
BEGIN DESCRIPTION:
Mapping XS 08fc8f5f
END DESCRIPTION:
XS GIS Cut Line= 3
      1651866.50      6963376.19      1652404.71      6963032.43
      1652696.40      6962709.49
#Sta/Elev= 30
  4367.8 1694.74  4394.0 1694.14  4409.2 1692.04  4472.8 1688.39  4567.7 1685.80
  4669.8 1678.41  4690.9 1678.18  4742.5 1672.63  4757.6 1672.18  4800.1 1662.03
  4847.0 1656.45  4857.6 1656.32  4878.8 1652.92  4923.7 1648.20  4930.4 1646.06
  4951.5 1643.13  4966.7 1636.33  4976.8 1635.68  4977.3 1635.18  4987.0 1635.68
  5005.9 1641.84  5010.4 1641.84  5016.7 1645.07  5051.7 1647.10  5116.1 1651.18
  5236.4 1661.29  5264.8 1665.52  5285.7 1670.79  5314.1 1675.32  5441.6 1686.52
#Mann=5,-1,0
  4367.8    0.07       0  4847.0   0.035       0  4976.8   0.035       0
  4987.0   0.035       0  5051.7    0.07       0
Bank Sta=4976.8,4987
Exp/Cntr=0.3,0.1

Type RM Length L Ch R = 1,5678,413,413,413
BEGIN DESCRIPTION:
Mapping XS a0b521b2
END DESCRIPTION:
XS GIS Cut Line= 3
      1651656.46      6964390.78      1652511.51      6963414.20
      1652680.78      6962810.91
#Sta/Elev= 30
  3685.1 1690.16  3871.0 1685.43  3948.3 1683.90  4132.4 1676.53  4430.4 1671.96
  4465.5 1668.98  4522.5 1668.78  4628.8 1664.63  4681.0 1660.26  4784.0 1654.17
  4790.5 1654.19  4961.9 1643.63  4982.0 1639.31  4998.1 1637.74  5015.0 1635.57
  5044.0 1635.10  5044.5 1634.60  5054.3 1635.10  5083.0 1638.09  5093.6 1642.59
  5122.5 1644.41  5127.7 1646.06  5161.8 1646.82  5280.4 1656.20  5421.1 1663.36
  5455.2 1666.91  5460.4 1669.03  5494.5 1672.87  5499.7 1674.78  5609.7 1681.32
#Mann=8,-1,0
  3685.1    0.16       0  3871.0    0.07       0  4681.0   0.035       0
  4784.0    0.07       0  4790.5   0.035       0  4998.1    0.07       0
  5044.0    0.07       0  5054.3    0.07       0
Bank Sta=5044,5054.3
Exp/Cntr=0.3,0.1

Type RM Length L Ch R = 1,5265,222,222,222
BEGIN DESCRIPTION:
Mapping XS 3f978eb6
END DESCRIPTION:
XS GIS Cut Line= 3
      1652273.94      6964011.01      1652657.60      6963764.49
      1652820.79      6963673.45
#Sta/Elev= 30
  4547.0 1657.68  4558.0 1657.03  4564.0 1657.72  4585.1 1657.19  4594.3 1656.18
  4600.3 1656.53  4615.5 1654.97  4636.6 1654.89  4667.0 1652.47  4672.9 1653.06
  4709.3 1650.05  4730.4 1649.80  4760.8 1647.77  4850.6 1644.06  4896.9 1642.29
  4933.2 1640.04  4940.5 1638.09  4954.3 1639.94  4969.5 1639.31  4976.2 1637.38
  4985.5 1635.86  4986.0 1635.36  4995.8 1635.86  5003.0 1636.09  5005.9 1637.42
  5011.7 1637.78  5034.4 1637.35  5065.4 1640.85  5108.8 1643.34  5189.9 1644.35
#Mann=4,-1,0
  4547.0    0.07       0  4850.6   0.035       0  4985.5   0.035       0
  4995.8   0.035       0
Bank Sta=4985.5,4995.8
Exp/Cntr=0.3,0.1

Type RM Length L Ch R = 1,5043,245,245,245
BEGIN DESCRIPTION:
Mapping XS b58ed3d7
END DESCRIPTION:
XS GIS Cut Line= 3
      1652376.40      6964109.96      1652701.00      6963974.56
      1652890.08      6963865.28
#Sta/Elev= 30
  4643.8 1650.20  4684.0 1648.66  4689.4 1648.78  4707.3 1647.64  4718.7 1646.42
  4737.1 1646.28  4742.1 1646.78  4798.6 1645.06  4867.0 1642.10  4872.5 1642.31
  4890.9 1641.44  4896.3 1641.74  4913.2 1641.23  4949.4 1639.57  4959.3 1638.21
  4967.3 1636.95  4983.9 1635.38  4984.4 1634.88  4993.7 1634.88  4994.2 1635.38
  4995.0 1635.85  5028.3 1637.00  5046.3 1636.76  5061.1 1637.68  5073.0 1637.81
  5082.7 1638.18  5092.5 1639.50  5098.4 1640.89  5180.4 1642.25  5213.9 1642.25
#Mann=9,-1,0
  4643.8    0.16       0  4742.1    0.07       0  4798.6    0.16       0
  4959.3   0.035       0  4983.9   0.035       0  4994.2   0.035       0
  5028.3    0.07       0  5073.0    0.16       0  5180.4   0.035       0
Bank Sta=4983.9,4994.2
Exp/Cntr=0.3,0.1

Type RM Length L Ch R = 1,4798,399,399,399
BEGIN DESCRIPTION:
Mapping XS 8cc8ad8a
END DESCRIPTION:
XS GIS Cut Line= 3
      1652321.65      6964353.47      1652799.09      6964186.37
      1652960.91      6964061.23
#Sta/Elev= 30
  4493.6 1649.22  4498.7 1649.55  4524.5 1648.11  4529.8 1648.42  4600.0 1646.55
  4746.9 1643.53  4793.1 1641.70  4798.4 1642.00  4824.2 1641.32  4855.2 1639.18
  4886.2 1638.03  4891.5 1638.76  4910.4 1638.36  4917.2 1637.64  4953.6 1636.92
  4963.3 1636.30  4979.3 1633.99  4984.6 1633.98  4997.6 1632.05  4998.1 1631.55
  5007.5 1631.55  5008.0 1632.05  5023.6 1633.47  5031.8 1635.86  5038.1 1636.33
  5044.8 1638.73  5078.3 1639.74  5108.7 1640.63  5145.9 1640.16  5204.0 1640.87
#Mann=6,-1,0
  4493.6    0.07       0  4600.0    0.16       0  4746.9    0.07       0
  4997.6    0.07       0  5008.0    0.07       0  5078.3    0.16       0
Bank Sta=4997.6,5008
Exp/Cntr=0.3,0.1

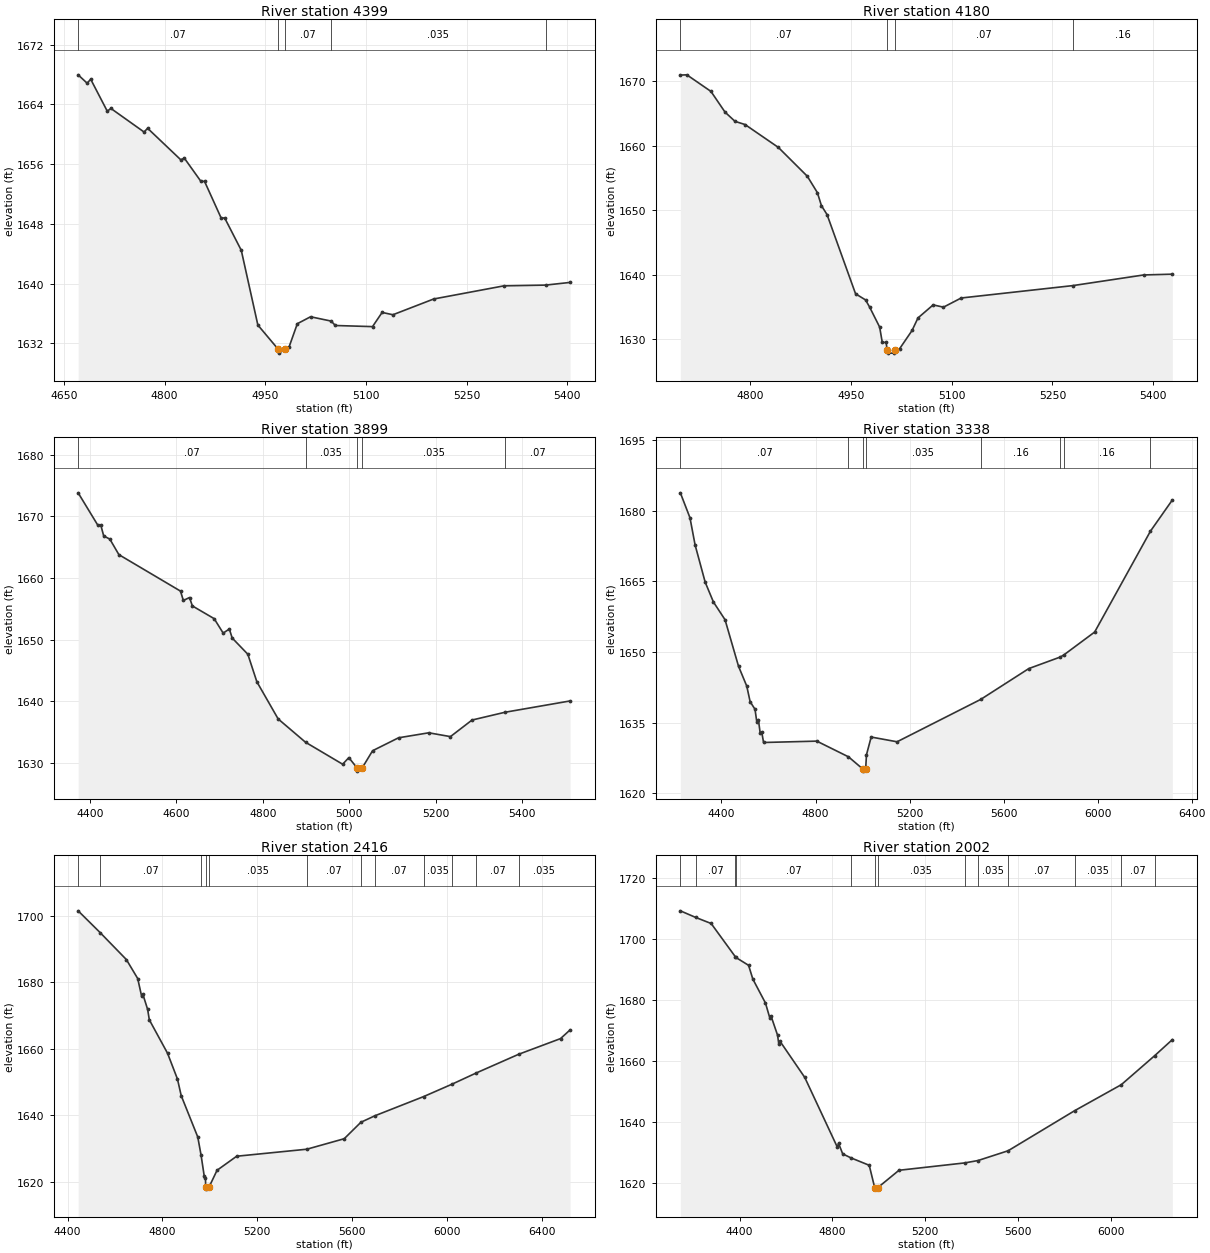
Type RM Length L Ch R = 1,4399,219,219,219
BEGIN DESCRIPTION:
Mapping XS 985d386c
END DESCRIPTION:
XS GIS Cut Line= 3
      1652703.62      6964811.34      1652820.80      6964505.38
      1652961.87      6964125.56
#Sta/Elev= 30
  4671.2 1667.96  4684.6 1666.84  4689.9 1667.37  4714.6 1663.09  4720.0 1663.46
  4769.4 1660.30  4774.7 1660.80  4824.1 1656.58  4829.4 1656.80  4854.1 1653.69
  4859.5 1653.69  4884.2 1648.79  4889.5 1648.79  4914.2 1644.46  4938.9 1634.45
  4969.4 1631.19  4969.9 1630.69  4979.8 1631.19  4985.3 1631.49  4997.7 1634.63
  5017.4 1635.56  5048.1 1634.98  5054.3 1634.39  5109.7 1634.24  5124.0 1636.14
  5140.1 1635.83  5200.8 1637.94  5305.4 1639.70  5367.5 1639.80  5404.0 1640.16
#Mann=5,-1,0
  4671.2    0.07       0  4969.4    0.07       0  4979.8    0.07       0
  5048.1   0.035       0  5367.5    0.16       0
Bank Sta=4969.4,4979.8
Exp/Cntr=0.3,0.1

Type RM Length L Ch R = 1,4180,281,281,281
BEGIN DESCRIPTION:
Mapping XS c688eb81
END DESCRIPTION:
XS GIS Cut Line= 3
      1652822.96      6964878.64      1652994.41      6964626.90
      1653120.13      6964217.24
#Sta/Elev= 30
  4695.6 1670.93  4705.3 1670.97  4741.2 1668.40  4762.2 1665.19  4777.1 1663.76
  4792.0 1663.27  4841.6 1659.73  4884.8 1655.26  4899.8 1652.72  4905.8 1650.71
  4914.2 1649.32  4956.7 1637.05  4971.6 1636.10  4977.6 1635.00  4992.6 1631.89
  4996.5 1629.52  5002.2 1629.52  5003.8 1628.36  5004.3 1627.86  5014.7 1627.86
  5015.2 1628.36  5022.2 1628.52  5040.9 1631.37  5049.7 1633.31  5072.3 1635.33
  5087.7 1634.98  5114.1 1636.40  5280.5 1638.32  5386.1 1639.97  5428.7 1640.09
#Mann=4,-1,0
  4695.6    0.07       0  5003.8    0.07       0  5015.2    0.07       0
  5280.5    0.16       0
Bank Sta=5003.8,5015.2
Exp/Cntr=0.3,0.1

Type RM Length L Ch R = 1,3899,561,561,561
BEGIN DESCRIPTION:
Mapping XS aca00f14
END DESCRIPTION:
XS GIS Cut Line= 3
      1652821.94      6965238.46      1653230.00      6964763.00
      1653208.89      6964251.20
#Sta/Elev= 30
  4372.6 1673.84  4417.5 1668.66  4425.2 1668.56  4431.8 1666.84  4446.0 1666.33
  4466.9 1663.81  4609.6 1657.89  4616.1 1656.37  4630.4 1656.85  4637.0 1655.49
  4687.5 1653.42  4708.3 1651.08  4722.6 1651.74  4729.2 1650.28  4765.4 1647.65
  4786.3 1643.18  4835.6 1637.15  4898.9 1633.37  4984.9 1629.80  4999.2 1630.87
  5018.5 1629.18  5019.0 1628.68  5029.9 1629.18  5054.2 1631.99  5114.3 1634.09
  5184.3 1634.90  5234.4 1634.28  5284.4 1636.97  5360.5 1638.23  5511.4 1640.07
#Mann=5,-1,0
  4372.6    0.07       0  4898.9   0.035       0  5018.5   0.035       0
  5029.9   0.035       0  5360.5    0.07       0
Bank Sta=5018.5,5029.9
Exp/Cntr=0.3,0.1

Type RM Length L Ch R = 1,3338,922,922,922
BEGIN DESCRIPTION:
Mapping XS 335a3c32
END DESCRIPTION:
XS GIS Cut Line= 3
      1652923.68      6965694.71      1653512.20      6965199.94
      1654835.10      6965153.06
#Sta/Elev= 30
  4225.1 1683.85  4266.0 1678.55  4287.8 1672.77  4330.7 1664.85  4365.8 1660.63
  4415.2 1656.86  4472.5 1646.97  4507.6 1642.74  4521.9 1639.43  4542.7 1637.81
  4550.5 1635.04  4557.0 1635.62  4564.8 1632.70  4571.3 1632.97  4579.1 1630.75
  4805.5 1631.04  4940.3 1627.70  5000.1 1625.16  5000.6 1624.66  5013.4 1625.16
  5016.8 1628.14  5036.8 1631.91  5146.9 1630.90  5503.0 1639.92  5707.2 1646.47
  5841.9 1648.94  5858.1 1649.44  5987.4 1654.24  6224.6 1675.69  6317.7 1682.32
#Mann=8,-1,0
  4225.1    0.07       0  4940.3   0.035       0  5000.1   0.035       0
  5013.4   0.035       0  5503.0    0.16       0  5841.9    0.07       0
  5858.1    0.16       0  6224.6    0.07       0
Bank Sta=5000.1,5013.4
Exp/Cntr=0.3,0.1

Type RM Length L Ch R = 1,2416,414,414,414
BEGIN DESCRIPTION:
Mapping XS e8b68091
END DESCRIPTION:
XS GIS Cut Line= 3
      1652775.23      6966124.07      1653303.00      6965957.40
      1654789.11      6965624.07
#Sta/Elev= 30
  4444.2 1701.53  4537.0 1694.98  4647.7 1686.87  4695.6 1681.16  4712.4 1675.76
  4717.6 1676.39  4737.6 1671.84  4744.7 1668.72  4821.5 1658.68  4863.4 1650.91
  4879.3 1645.90  4949.2 1633.45  4963.0 1628.04  4976.3 1621.76  4981.6 1621.20
  4982.6 1618.28  4983.1 1617.78  4996.0 1618.28  5030.5 1623.45  5113.4 1627.68
  5409.4 1629.79  5567.3 1632.95  5637.7 1637.90  5697.0 1639.86  5902.5 1645.63
  6022.2 1649.36  6124.4 1652.73  6303.5 1658.36  6480.3 1663.08  6520.7 1665.70
#Mann=12,-1,0
  4444.2    0.16       0  4537.0    0.07       0  4963.0   0.035       0
  4982.6   0.035       0  4996.0   0.035       0  5409.4    0.07       0
  5637.7   0.035       0  5697.0    0.07       0  5902.5   0.035       0
  6022.2    0.16       0  6124.4    0.07       0  6303.5   0.035       0
Bank Sta=4982.6,4996
Exp/Cntr=0.3,0.1

Type RM Length L Ch R = 1,2002,658,658,658
BEGIN DESCRIPTION:
Mapping XS eddf16dc
END DESCRIPTION:
XS GIS Cut Line= 3
      1652532.18      6966589.34      1653348.14      6966356.71
      1654577.27      6966030.33
#Sta/Elev= 30
  4144.8 1709.26  4210.9 1707.09  4277.5 1705.10  4382.3 1694.12  4383.3 1693.98
  4438.9 1691.36  4457.1 1686.85  4511.7 1678.96  4530.0 1674.15  4535.2 1674.79
  4563.7 1668.42  4569.0 1665.53  4574.2 1666.42  4680.9 1654.54  4821.4 1631.62
  4826.6 1632.91  4844.4 1629.42  4880.3 1628.10  4958.8 1625.67  4982.3 1618.34
  4982.8 1617.84  4995.8 1618.34  5087.0 1624.03  5370.3 1626.45  5427.5 1627.23
  5557.3 1630.44  5843.7 1643.59  6045.0 1652.14  6189.8 1661.73  6265.0 1666.94
#Mann=13,-1,0
  4144.8   0.035       0  4210.9    0.07       0  4382.3    0.16       0
  4383.3    0.07       0  4880.3   0.035       0  4982.3   0.035       0
  4995.8   0.035       0  5370.3    0.07       0  5427.5   0.035       0
  5557.3    0.07       0  5843.7   0.035       0  6045.0    0.07       0
  6189.8   0.035       0
Bank Sta=4982.3,4995.8
Exp/Cntr=0.3,0.1

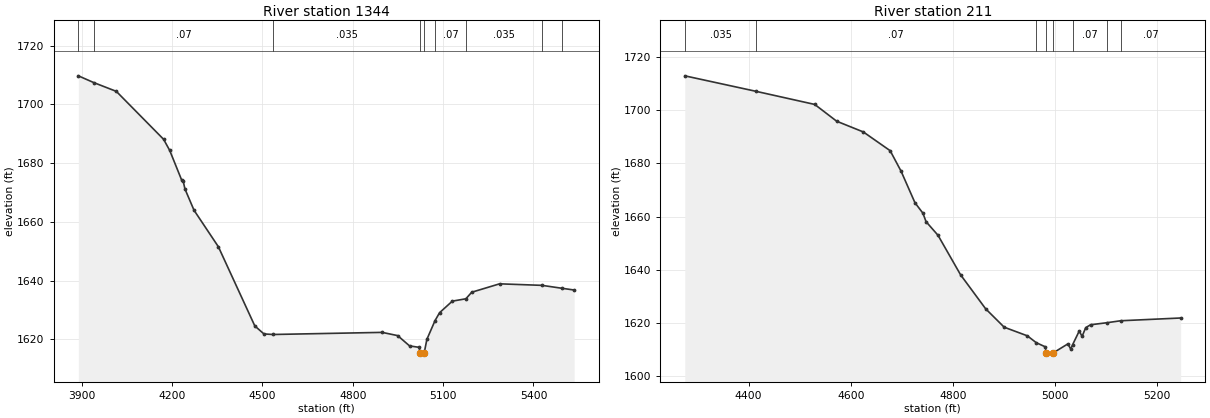
Type RM Length L Ch R = 1,1344,1133,1133,1133
BEGIN DESCRIPTION:
Mapping XS 98883f43
END DESCRIPTION:
XS GIS Cut Line= 3
      1652504.40      6966756.02      1653598.14      6966905.32
      1654125.95      6966780.31
#Sta/Elev= 30
  3888.9 1709.69  3940.1 1707.39  4015.1 1704.40  4172.1 1688.08  4192.3 1684.31
  4231.9 1674.25  4237.0 1673.92  4242.8 1671.22  4273.0 1663.96  4353.8 1651.55
  4474.9 1624.59  4505.2 1621.87  4535.0 1621.68  4897.7 1622.40  4949.2 1621.30
  4988.7 1617.80  5020.4 1617.31  5023.9 1615.50  5024.4 1615.00  5037.5 1615.50
  5046.2 1620.03  5073.3 1626.41  5088.4 1629.10  5130.7 1633.03  5175.7 1633.83
  5195.1 1636.06  5287.6 1638.92  5428.2 1638.40  5495.8 1637.39  5535.2 1636.81
#Mann=9,-1,0
  3888.9   0.035       0  3940.1    0.07       0  4535.0   0.035       0
  5023.9   0.035       0  5037.5   0.035       0  5073.3    0.07       0
  5175.7   0.035       0  5428.2    0.07       0  5495.8   0.035       0
Bank Sta=5023.9,5037.5
Exp/Cntr=0.3,0.1

Type RM Length L Ch R = 1,211,0,0,0
BEGIN DESCRIPTION:
Chimney Creek 1142 1.0
END DESCRIPTION:
XS GIS Cut Line= 3
      1652329.99      6967162.99      1652951.47      6967536.54
      1653170.28      6967424.11
#Sta/Elev= 30
  4274.9 1713.00  4414.8 1707.15  4529.4 1702.23  4572.4 1695.91  4624.6 1691.87
  4677.1 1684.82  4698.5 1677.10  4725.7 1665.22  4741.2 1661.31  4747.4 1658.11
  4770.8 1652.98  4815.0 1638.11  4864.1 1625.31  4900.5 1618.37  4945.8 1615.13
  4963.3 1612.54  4980.8 1611.00  4983.1 1608.74  4983.6 1608.24  4996.7 1608.74
  5025.2 1612.10  5030.8 1610.14  5034.5 1611.80  5047.4 1616.93  5053.0 1614.93
  5060.2 1618.22  5069.6 1619.29  5102.4 1620.08  5128.5 1620.80  5246.0 1621.84
#Mann=8,-1,0
  4274.9   0.035       0  4414.8    0.07       0  4963.3   0.035       0
  4983.1   0.035       0  4996.7   0.035       0  5034.5    0.07       0
  5102.4   0.035       0  5128.5    0.07       0
Bank Sta=4983.1,4996.7
Exp/Cntr=0.3,0.1

Chan Stop Cuts=-1