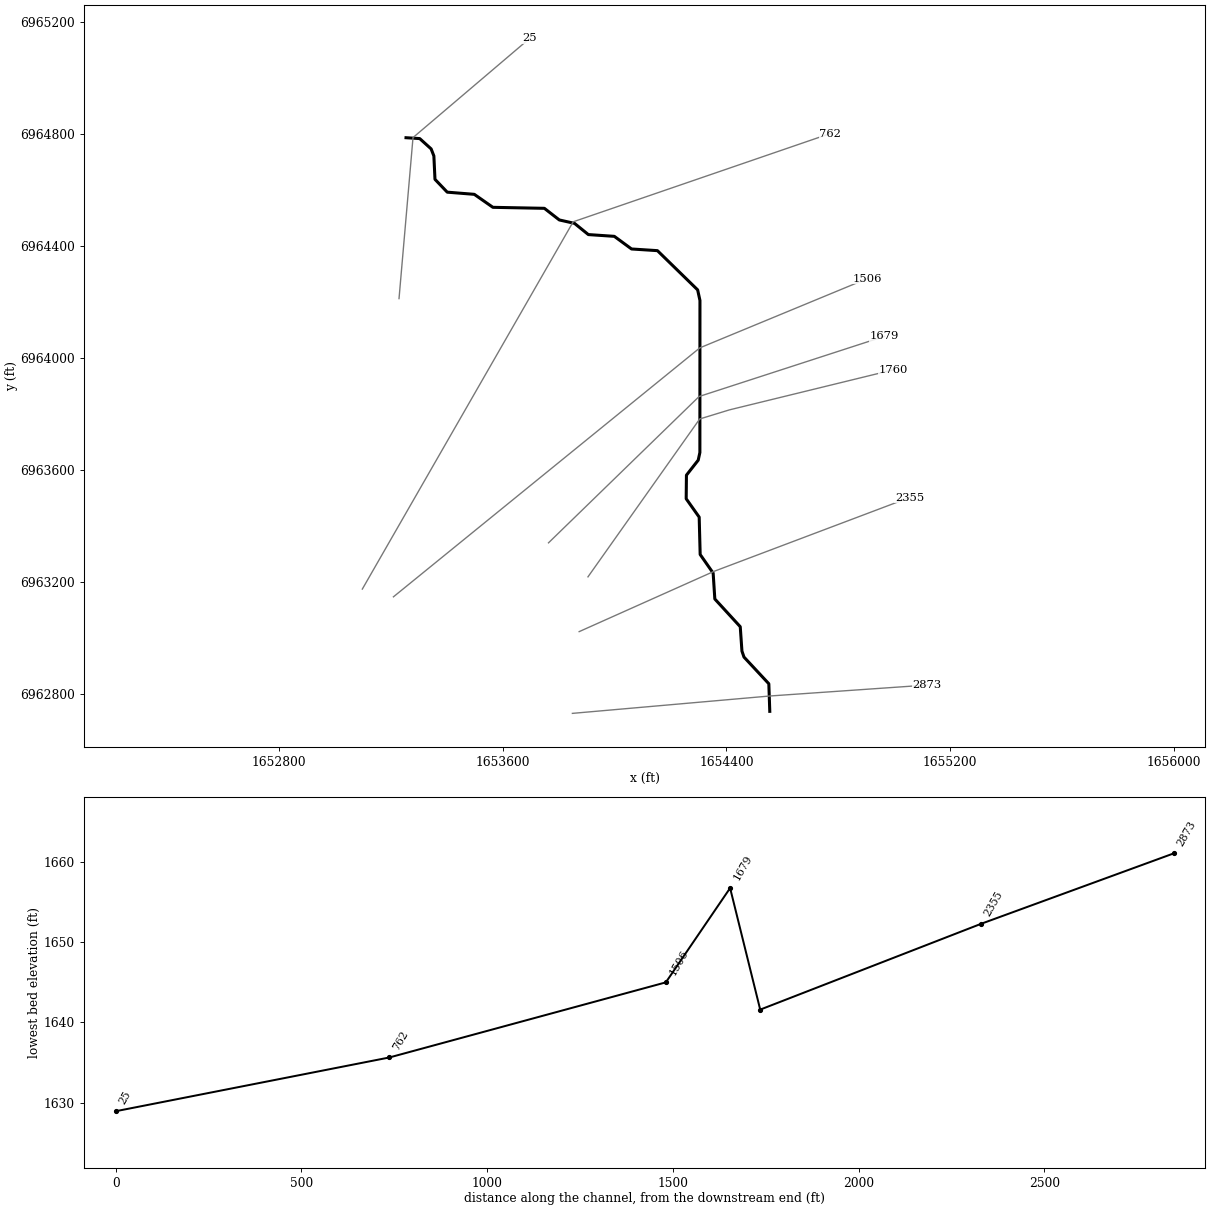
--- Chimney Creek 1143.prj (project) ---

Proj Title=Chimney Creek 1143 Base Level Engineering
Current Plan=p01
Default Exp/Contr=0.3,0.1
English Units
Geom File=g01
Flow File=f01
Plan File=p01
BEGIN DESCRIPTION:
Chimney Creek 1143
END DESCRIPTION:

--- Chimney Creek 1143.p01 (plan) ---

Plan Title=Multiple Run
Short Identifier=Multiple
Geom File=g01
Flow File=f01
Subcritical Flow
K Sum by GR= 0
Std Step Tol= 0.01
Critical Tol= 0.01
Num of Std Step Trials= 20
Max Error Tol= 0.3
Flow Tol Ratio= 0.001
Split Flow NTrial= 30
Split Flow Tol= 0.02
Split Flow Ratio= 0.02
Log Output Level= 0
Friction Slope Method= 1
Unsteady Friction Slope Method= 2
Unsteady Bridges Friction Slope Method= 1
Parabolic Critical Depth
Global Vel Dist=  1 , 1 , 1
Global Log Level= 0
CheckData=True
Encroach Param= -1, 0, 0, 0
BEGIN DESCRIPTION:
Multiple Run
END DESCRIPTION:

--- Chimney Creek 1143.f01 (steady flow) ---

Flow Title=Multiple
Number of Profiles=7
Profile Names=10-year,25-year,50-year,1pct_min,100-year,1pct_plu,500-year
River Rch & RM= Chimney Creek 11,Reach-1,2873
     238     327     401     245     489     977     737
River Rch & RM= Chimney Creek 11,Reach-1,1760
     260     362     445     274     546    1089     830
Boundary for River Rch & Prof#=Chimney Creek 11,Reach-1,1
Up Type=0
Dn Type=3
Dn Slope=0.005
Boundary for River Rch & Prof#=Chimney Creek 11,Reach-1,2
Up Type=0
Dn Type=3
Dn Slope=0.005
Boundary for River Rch & Prof#=Chimney Creek 11,Reach-1,3
Up Type=0
Dn Type=3
Dn Slope=0.005
Boundary for River Rch & Prof#=Chimney Creek 11,Reach-1,4
Up Type=0
Dn Type=3
Dn Slope=0.005
Boundary for River Rch & Prof#=Chimney Creek 11,Reach-1,5
Up Type=0
Dn Type=3
Dn Slope=0.005
Boundary for River Rch & Prof#=Chimney Creek 11,Reach-1,6
Up Type=0
Dn Type=3
Dn Slope=0.005
Boundary for River Rch & Prof#=Chimney Creek 11,Reach-1,7
Up Type=0
Dn Type=3
Dn Slope=0.005

--- Chimney Creek 1143.g01 (geometry) ---

Geom Title=Existing Conditions

River Reach=Chimney Creek 11,Reach-1
Reach XY= 30
      1654555.00      6962738.00      1654551.61      6962836.59
      1654462.88      6962931.84      1654455.53      6962953.22
      1654449.46      6963040.42      1654358.62      6963139.50
      1654352.64      6963232.02      1654306.23      6963298.51
      1654302.73      6963432.06      1654256.27      6963497.71
      1654257.17      6963582.02      1654299.25      6963635.66
      1654305.20      6963662.92      1654305.46      6964206.37
      1654297.19      6964244.19      1654153.50      6964384.39
      1654060.98      6964390.36      1653999.43      6964435.53
      1653906.58      6964441.83      1653857.18      6964481.89
      1653802.82      6964494.12      1653749.48      6964535.65
      1653565.50      6964539.22      1653499.02      6964585.64
      1653402.29      6964593.40      1653358.51      6964639.25
      1653354.53      6964722.88      1653344.73      6964748.09
      1653304.01      6964784.88      1653255.00      6964788.00

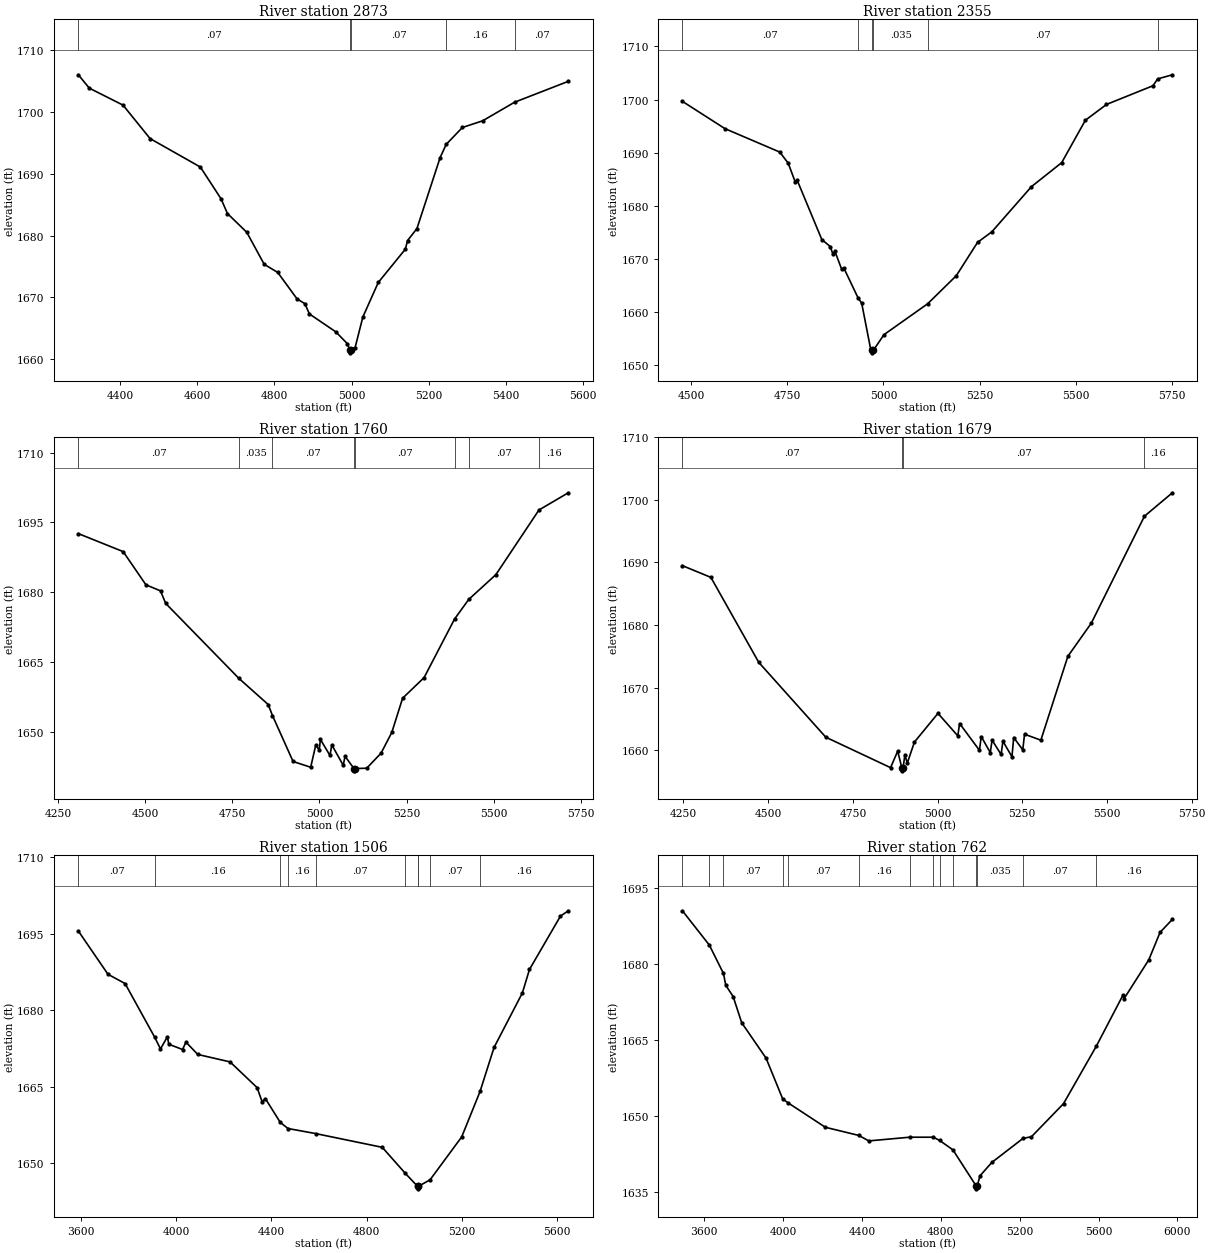
Type RM Length L Ch R = 1,2873,518,518,518
BEGIN DESCRIPTION:
Chimney Creek 1143 4.0
END DESCRIPTION:
XS GIS Cut Line= 3
      1653849.58      6962730.71      1654555.75      6962792.86
      1655116.90      6962831.88
#Sta/Elev= 30
  4291.1 1706.02  4319.4 1703.86  4407.0 1701.11  4477.2 1695.70  4607.7 1691.09
  4661.2 1685.97  4678.0 1683.57  4728.2 1680.53  4773.4 1675.35  4808.5 1674.04
  4858.7 1669.75  4878.8 1668.99  4890.7 1667.32  4959.1 1664.43  4989.2 1662.51
  4995.1 1661.53  4995.4 1661.03  4999.1 1661.53  5009.3 1661.89  5029.3 1666.82
  5069.4 1672.42  5139.6 1677.80  5145.4 1679.20  5169.7 1681.14  5229.8 1692.61
  5245.5 1694.75  5287.6 1697.49  5340.1 1698.57  5423.1 1701.58  5562.5 1704.96
#Mann=5,-1,0
  4291.1    0.07       0  4995.1    0.07       0  4999.1    0.07       0
  5245.5    0.16       0  5423.1    0.07       0
Bank Sta=4995.1,4999.1
Exp/Cntr=0.3,0.1

Type RM Length L Ch R = 1,2355,595,595,595
BEGIN DESCRIPTION:
Chimney Creek 1143 3.0
END DESCRIPTION:
XS GIS Cut Line= 3
      1653873.82      6963022.85      1654355.00      6963238.00
      1655054.34      6963502.01
#Sta/Elev= 30
  4477.1 1699.65  4587.9 1694.51  4730.3 1690.10  4752.3 1688.01  4770.1 1684.55
  4775.5 1684.82  4839.7 1673.63  4861.8 1672.29  4868.4 1670.91  4873.8 1671.42
  4891.6 1667.98  4897.0 1668.26  4934.5 1662.56  4943.4 1661.66  4966.6 1653.05
  4970.1 1652.78  4970.4 1652.28  4974.1 1652.78  5001.4 1655.70  5115.2 1661.53
  5189.7 1666.82  5244.8 1673.08  5282.1 1675.08  5385.0 1683.58  5463.8 1688.11
  5525.3 1696.09  5580.3 1699.07  5701.1 1702.59  5713.5 1703.88  5751.7 1704.66
#Mann=6,-1,0
  4477.1    0.07       0  4934.5   0.035       0  4970.1   0.035       0
  4974.1   0.035       0  5115.2    0.07       0  5713.5    0.16       0
Bank Sta=4970.1,4974.1
Exp/Cntr=0.3,0.1

Type RM Length L Ch R = 1,1760,81,81,81
BEGIN DESCRIPTION:
Mapping XS 7dbc37a4
END DESCRIPTION:
XS GIS Cut Line= 4
      1653905.27      6963218.62      1654304.56      6963782.83
      1654410.89      6963815.39      1654996.82      6963958.61
#Sta/Elev= 30
  4308.3 1692.60  4436.9 1688.73  4502.2 1681.59  4544.0 1680.29  4558.8 1677.60
  4769.1 1661.46  4852.9 1655.86  4865.2 1653.49  4924.3 1643.61  4974.8 1642.37
  4989.5 1647.18  4999.5 1646.03  5002.6 1648.37  5030.2 1644.90  5035.4 1647.18
  5068.2 1642.79  5073.4 1644.73  5098.9 1642.10  5099.2 1641.60  5102.9 1642.10
  5135.5 1642.16  5176.7 1645.40  5207.6 1649.87  5238.5 1657.21  5300.2 1661.65
  5387.5 1674.23  5428.2 1678.45  5506.1 1683.78  5629.7 1697.68  5713.9 1701.38
#Mann=8,-1,0
  4308.3    0.07       0  4769.1   0.035       0  4865.2    0.07       0
  5098.9    0.07       0  5102.9    0.07       0  5387.5    0.16       0
  5428.2    0.07       0  5629.7    0.16       0
Bank Sta=5098.9,5102.9
Exp/Cntr=0.3,0.1

Type RM Length L Ch R = 1,1679,173,173,173
BEGIN DESCRIPTION:
Mapping XS a212fb14
END DESCRIPTION:
XS GIS Cut Line= 3
      1653764.21      6963340.15      1654302.38      6963863.13
      1654964.26      6964077.97
#Sta/Elev= 30
  4246.8 1689.49  4330.8 1687.62  4472.1 1674.05  4670.1 1662.09  4861.2 1657.23
  4882.3 1659.86  4894.4 1657.22  4894.7 1656.72  4898.4 1657.22  4903.4 1659.26
  4910.6 1657.95  4931.7 1661.32  5001.2 1665.90  5059.7 1662.31  5065.0 1664.28
  5123.6 1660.00  5128.9 1662.20  5155.6 1659.63  5160.9 1661.63  5187.6 1659.33
  5192.8 1661.46  5219.5 1658.97  5224.8 1662.04  5251.5 1660.07  5256.7 1662.57
  5304.9 1661.62  5384.6 1675.01  5453.8 1680.31  5610.7 1697.39  5693.1 1701.13
#Mann=4,-1,0
  4246.8    0.07       0  4894.4    0.07       0  4898.4    0.07       0
  5610.7    0.16       0
Bank Sta=4894.4,4898.4
Exp/Cntr=0.3,0.1

Type RM Length L Ch R = 1,1506,744,744,744
BEGIN DESCRIPTION:
Mapping XS a84451fc
END DESCRIPTION:
XS GIS Cut Line= 3
      1653210.03      6963147.22      1654305.01      6964036.96
      1654903.28      6964284.35
#Sta/Elev= 30
  3589.1 1695.54  3713.6 1687.06  3785.4 1685.24  3909.9 1674.71  3934.1 1672.42
  3962.9 1674.78  3969.3 1673.34  4026.8 1672.31  4041.2 1673.76  4090.7 1671.34
  4226.5 1669.88  4340.0 1664.84  4360.8 1662.09  4375.2 1662.65  4437.4 1658.02
  4469.8 1656.82  4585.5 1655.83  4865.8 1653.13  4962.0 1648.06  5014.0 1645.49
  5014.3 1644.99  5018.0 1645.49  5066.8 1646.77  5199.6 1655.18  5276.7 1664.09
  5335.4 1672.71  5454.5 1683.41  5484.2 1688.00  5614.5 1698.47  5647.4 1699.51
#Mann=10,-1,0
  3589.1    0.07       0  3909.9    0.16       0  4437.4    0.07       0
  4469.8    0.16       0  4585.5    0.07       0  4962.0   0.035       0
  5014.0   0.035       0  5018.0   0.035       0  5066.8    0.07       0
  5276.7    0.16       0
Bank Sta=5014,5018
Exp/Cntr=0.3,0.1

Type RM Length L Ch R = 1,762,737,737,737
BEGIN DESCRIPTION:
Mapping XS ad1f69c0
END DESCRIPTION:
XS GIS Cut Line= 3
      1653098.86      6963174.94      1653852.35      6964487.47
      1654770.59      6964802.79
#Sta/Elev= 30
  3489.8 1690.53  3626.3 1683.76  3697.9 1678.16  3709.8 1675.81  3747.0 1673.61
  3790.4 1668.43  3914.0 1661.44  3998.3 1653.40  4024.4 1652.65  4214.6 1647.80
  4384.5 1646.19  4434.6 1645.11  4641.9 1645.84  4762.5 1645.84  4793.9 1645.20
  4861.3 1643.35  4980.4 1636.15  4980.7 1635.65  4984.5 1636.15  4998.3 1638.21
  5058.9 1640.87  5216.7 1645.60  5259.8 1645.94  5422.1 1652.46  5588.4 1663.80
  5724.1 1673.92  5729.4 1673.20  5854.4 1680.84  5911.6 1686.26  5974.1 1688.84
#Mann=14,-1,0
  3489.8    0.07       0  3626.3    0.16       0  3697.9    0.07       0
  3998.3   0.035       0  4024.4    0.07       0  4384.5    0.16       0
  4641.9    0.07       0  4762.5   0.035       0  4793.9    0.07       0
  4861.3   0.035       0  4980.4   0.035       0  4984.5   0.035       0
  5216.7    0.07       0  5588.4    0.16       0
Bank Sta=4980.4,4984.5
Exp/Cntr=0.3,0.1

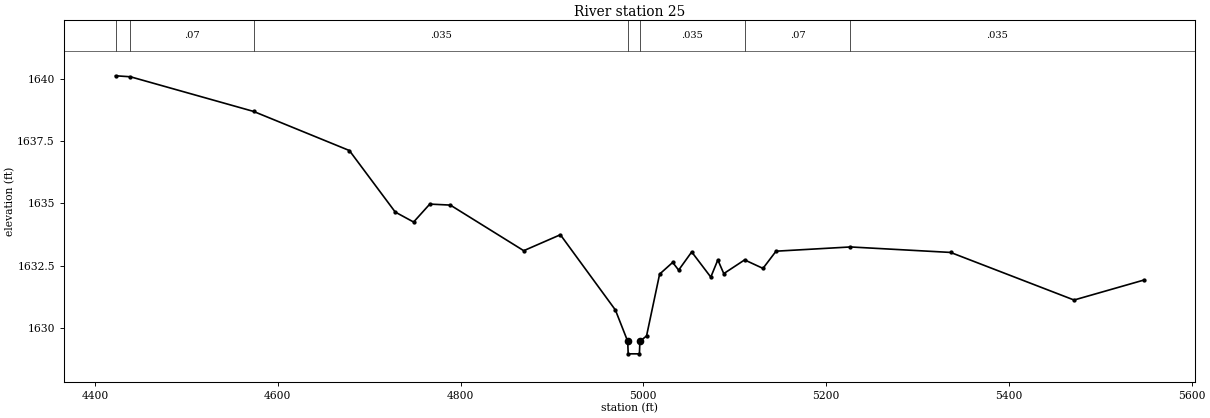
Type RM Length L Ch R = 1,25,0,0,0
BEGIN DESCRIPTION:
Chimney Creek 1143 1.0
END DESCRIPTION:
XS GIS Cut Line= 3
      1653230.00      6964213.02      1653280.00      6964788.46
      1653697.20      6965143.15
#Sta/Elev= 30
  4422.4 1640.12  4438.7 1640.08  4573.4 1638.69  4678.3 1637.12  4728.5 1634.65
  4748.6 1634.25  4766.3 1634.97  4788.8 1634.93  4869.1 1633.10  4909.2 1633.74
  4969.4 1630.72  4982.9 1629.46  4983.4 1628.96  4995.7 1628.96  4996.2 1629.46
  5003.5 1629.68  5017.8 1632.16  5032.1 1632.63  5038.6 1632.32  5052.9 1633.05
  5073.8 1632.04  5081.5 1632.73  5088.0 1632.18  5110.8 1632.73  5130.9 1632.39
  5145.2 1633.08  5226.6 1633.25  5336.2 1633.03  5471.3 1631.12  5547.6 1631.92
#Mann=7,-1,0
  4422.4   0.035       0  4438.7    0.07       0  4573.4   0.035       0
  4982.9   0.035       0  4996.2   0.035       0  5110.8    0.07       0
  5226.6   0.035       0
Bank Sta=4982.9,4996.2
Exp/Cntr=0.3,0.1

Chan Stop Cuts=-1