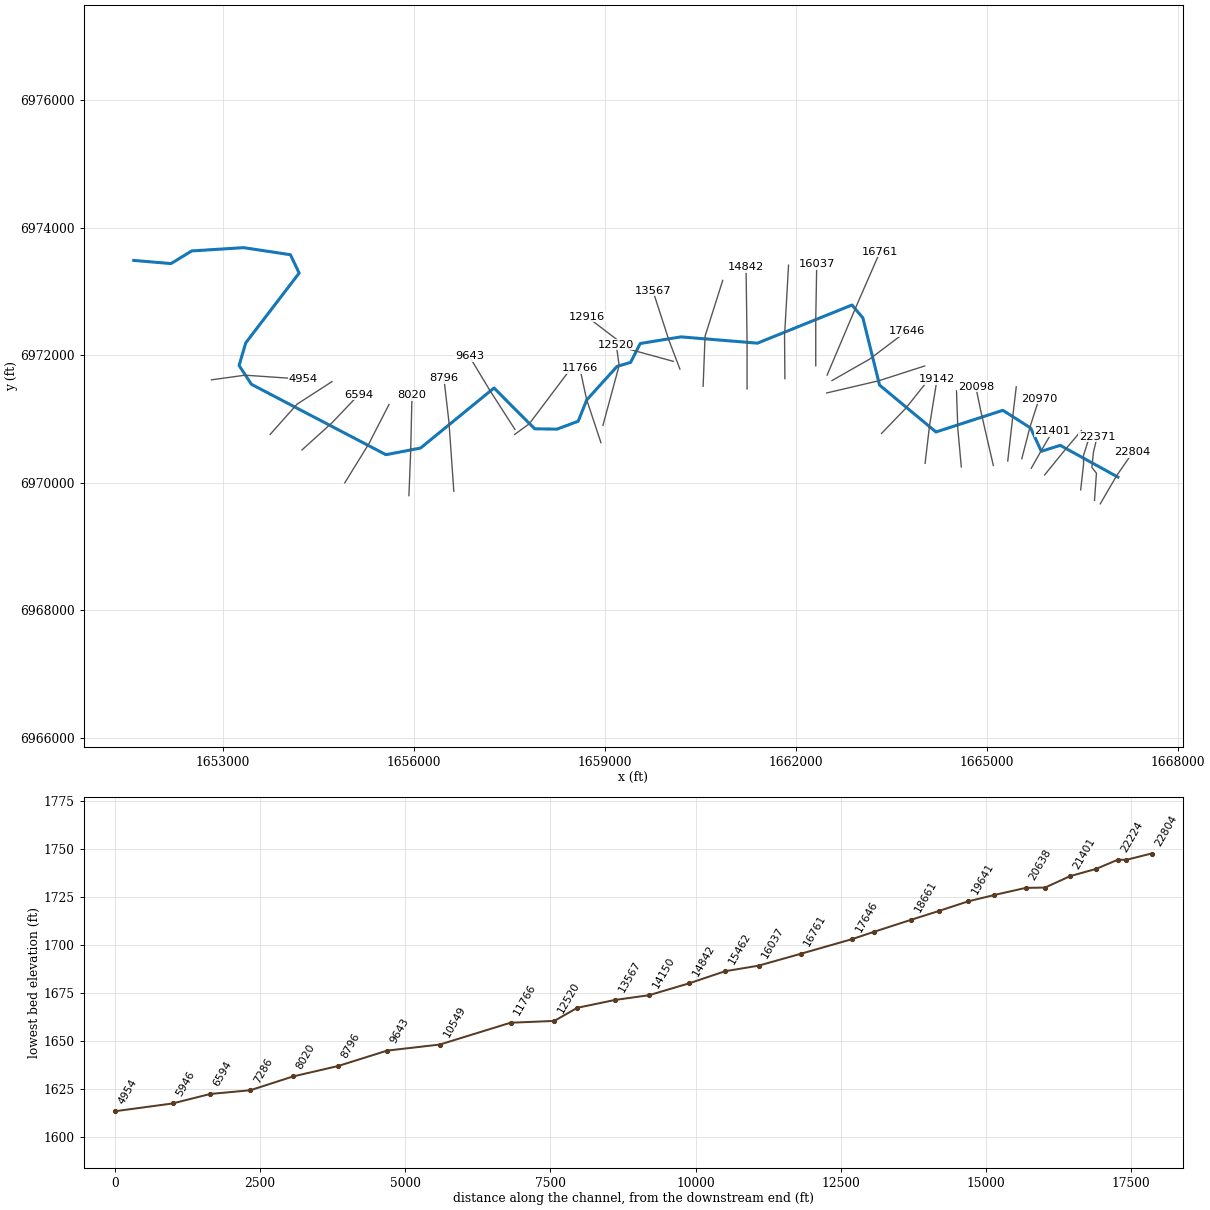
--- Chimney Creek 1144.prj (project) ---

Proj Title=Chimney Creek 1144 Base Level Engineering
Current Plan=p01
Default Exp/Contr=0.3,0.1
English Units
Geom File=g01
Flow File=f01
Plan File=p01
BEGIN DESCRIPTION:
Chimney Creek 1144
END DESCRIPTION:

--- Chimney Creek 1144.p01 (plan) ---

Plan Title=Multiple Run
Short Identifier=Multiple
Geom File=g01
Flow File=f01
Subcritical Flow
K Sum by GR= 0
Std Step Tol= 0.01
Critical Tol= 0.01
Num of Std Step Trials= 20
Max Error Tol= 0.3
Flow Tol Ratio= 0.001
Split Flow NTrial= 30
Split Flow Tol= 0.02
Split Flow Ratio= 0.02
Log Output Level= 0
Friction Slope Method= 1
Unsteady Friction Slope Method= 2
Unsteady Bridges Friction Slope Method= 1
Parabolic Critical Depth
Global Vel Dist=  1 , 1 , 1
Global Log Level= 0
CheckData=True
Encroach Param= -1, 0, 0, 0
BEGIN DESCRIPTION:
Multiple Run
END DESCRIPTION:

--- Chimney Creek 1144.f01 (steady flow) ---

Flow Title=Multiple
Number of Profiles=7
Profile Names=10-year,25-year,50-year,1pct_min,100-year,1pct_plu,500-year
River Rch & RM= Chimney Creek 11,Reach-1,22804
     213     290     352     214     426     850     631
River Rch & RM= Chimney Creek 11,Reach-1,20970
     359     505     627     388     774    1544    1193
River Rch & RM= Chimney Creek 11,Reach-1,12520
     665     966    1225     772    1541    3074    2469
River Rch & RM= Chimney Creek 11,Reach-1,6594
     719    1048    1333     842    1680    3352    2705
Boundary for River Rch & Prof#=Chimney Creek 11,Reach-1,1
Up Type=0
Dn Type=3
Dn Slope=0.005
Boundary for River Rch & Prof#=Chimney Creek 11,Reach-1,2
Up Type=0
Dn Type=3
Dn Slope=0.005
Boundary for River Rch & Prof#=Chimney Creek 11,Reach-1,3
Up Type=0
Dn Type=3
Dn Slope=0.005
Boundary for River Rch & Prof#=Chimney Creek 11,Reach-1,4
Up Type=0
Dn Type=3
Dn Slope=0.005
Boundary for River Rch & Prof#=Chimney Creek 11,Reach-1,5
Up Type=0
Dn Type=3
Dn Slope=0.005
Boundary for River Rch & Prof#=Chimney Creek 11,Reach-1,6
Up Type=0
Dn Type=3
Dn Slope=0.005
Boundary for River Rch & Prof#=Chimney Creek 11,Reach-1,7
Up Type=0
Dn Type=3
Dn Slope=0.005

--- Chimney Creek 1144.g01 (geometry) ---

Geom Title=Existing Conditions

River Reach=Chimney Creek 11,Reach-1
Reach XY= 30
      1667055.00      6970088.00      1666149.14      6970585.95
      1665852.46      6970492.96      1665685.37      6970858.16
      1665249.07      6971135.76      1664198.81      6970795.83
      1663313.14      6971531.94      1663051.18      6972586.42
      1662880.12      6972788.30      1661395.34      6972189.38
      1660195.72      6972288.45      1659556.55      6972184.25
      1659405.00      6971888.00      1659191.70      6971824.60
      1658715.76      6971297.68      1658582.19      6970964.05
      1658249.06      6970840.26      1657898.81      6970845.81
      1657261.12      6971486.18      1656107.43      6970543.52
      1655564.65      6970439.36      1653452.69      6971543.82
      1653258.67      6971839.58      1653363.16      6972194.05
      1654201.53      6973289.50      1654064.70      6973577.24
      1653329.92      6973688.20      1652515.50      6973636.80
      1652189.84      6973438.39      1651605.00      6973488.00

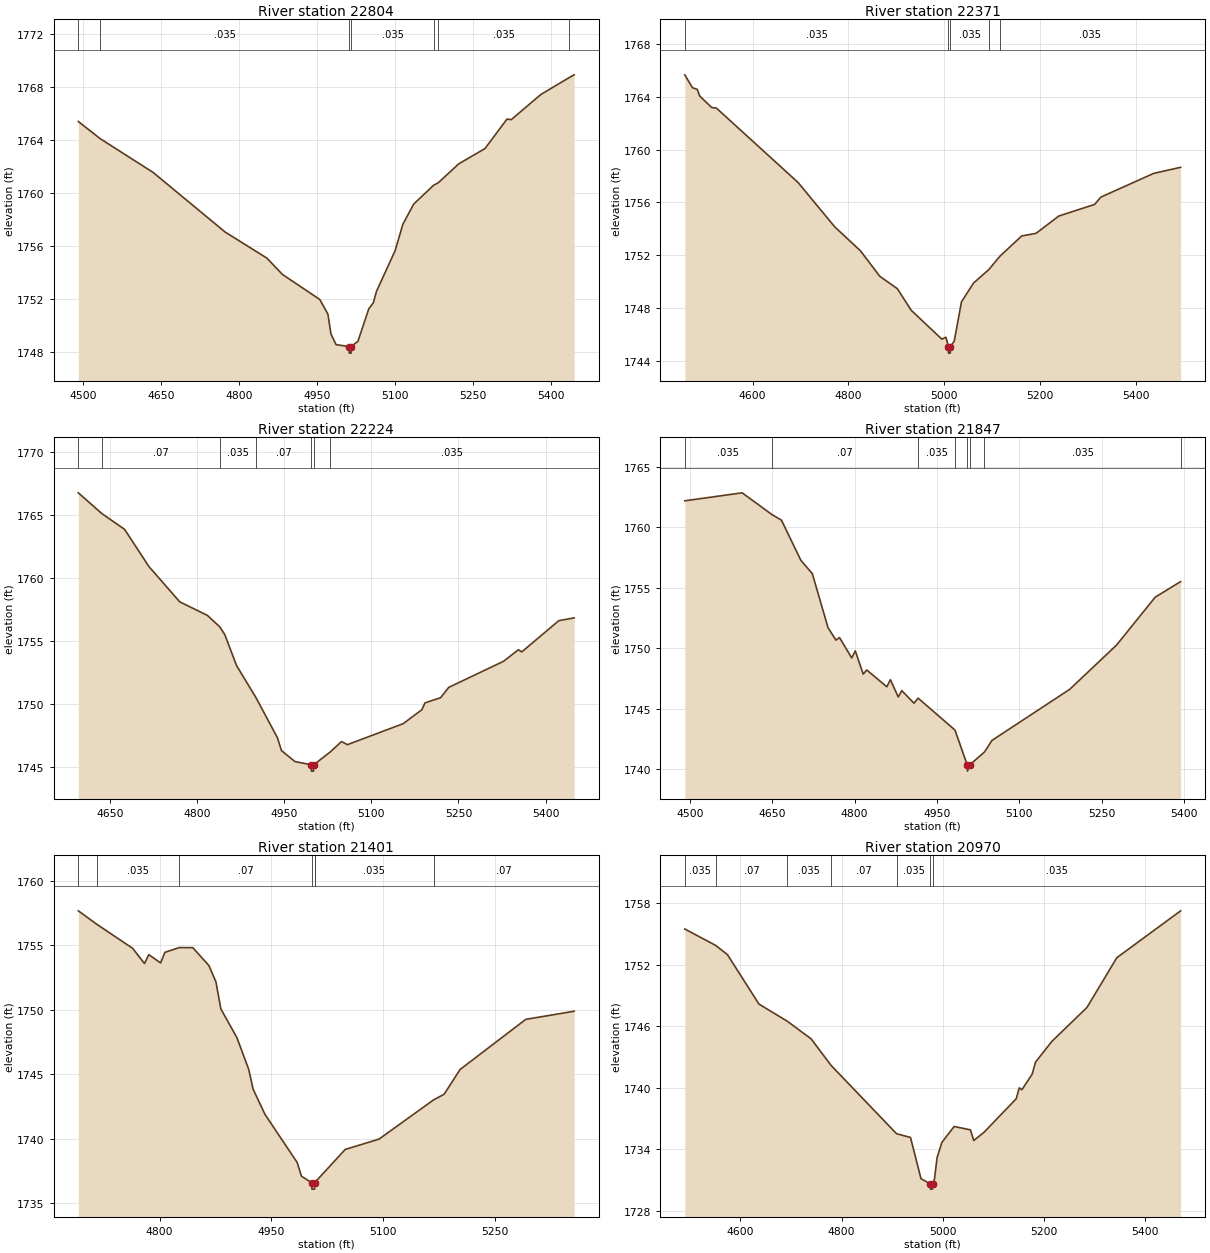
Type RM Length L Ch R = 1,22804,433,433,433
BEGIN DESCRIPTION:
Chimney Creek 1144 50.0
END DESCRIPTION:
XS GIS Cut Line= 3
      1666778.01      6969668.32      1667034.38      6970108.74
      1667287.55      6970474.34
#Sta/Elev= 30
  4490.4 1765.41  4532.1 1764.12  4634.1 1761.56  4773.1 1757.04  4853.3 1755.07
  4883.4 1753.83  4955.1 1751.94  4970.8 1750.83  4976.6 1749.33  4986.5 1748.52
  5011.6 1748.38  5011.9 1747.88  5015.4 1747.88  5015.6 1748.38  5028.5 1748.77
  5049.4 1751.23  5058.2 1751.69  5064.3 1752.56  5100.1 1755.63  5115.0 1757.63
  5135.9 1759.16  5174.4 1760.59  5183.1 1760.77  5222.4 1762.20  5273.1 1763.36
  5315.4 1765.59  5323.7 1765.55  5380.5 1767.45  5435.5 1768.74  5444.7 1768.94
#Mann=7,-1,0
  4490.4    0.07       0  4532.1   0.035       0  5011.6   0.035       0
  5015.6   0.035       0  5174.4    0.07       0  5183.1   0.035       0
  5435.5    0.07       0
Bank Sta=5011.6,5015.6
Exp/Cntr=0.3,0.1

Type RM Length L Ch R = 1,22371,147,147,147
BEGIN DESCRIPTION:
Mapping XS fe4ed71f
END DESCRIPTION:
XS GIS Cut Line= 5
      1666687.75      6969722.16      1666718.14      6970149.69
      1666646.52      6970238.66      1666670.39      6970475.21
      1666728.99      6970722.60
#Sta/Elev= 30
  4458.6 1765.66  4474.5 1764.69  4484.5 1764.56  4489.9 1764.05  4514.6 1763.19
  4524.6 1763.14  4695.0 1757.51  4771.3 1754.16  4825.4 1752.33  4865.5 1750.41
  4902.2 1749.47  4931.0 1747.84  4995.0 1745.65  5003.6 1745.79  5008.8 1745.09
  5009.1 1744.59  5012.6 1744.59  5012.8 1745.09  5020.9 1745.49  5036.0 1748.47
  5061.1 1749.89  5093.5 1750.93  5116.1 1751.92  5161.6 1753.46  5191.7 1753.66
  5239.2 1754.97  5314.0 1755.85  5326.8 1756.40  5437.3 1758.20  5493.4 1758.66
#Mann=5,-1,0
  4458.6   0.035       0  5008.8   0.035       0  5012.8   0.035       0
  5093.5    0.07       0  5116.1   0.035       0
Bank Sta=5008.8,5012.8
Exp/Cntr=0.3,0.1

Type RM Length L Ch R = 1,22224,377,377,377
BEGIN DESCRIPTION:
Mapping XS 9f1bba08
END DESCRIPTION:
XS GIS Cut Line= 4
      1666470.74      6969887.08      1666516.31      6970292.92
      1666514.14      6970425.30      1666609.35      6970723.90
#Sta/Elev= 30
  4595.1 1766.75  4635.7 1765.10  4674.8 1763.85  4716.8 1760.89  4769.9 1758.09
  4817.4 1757.02  4838.5 1756.12  4847.6 1755.48  4867.7 1753.03  4901.0 1750.50
  4938.2 1747.29  4945.1 1746.28  4968.3 1745.41  4996.5 1745.15  4996.7 1744.65
  5000.2 1744.65  5000.5 1745.15  5028.5 1746.15  5048.6 1747.00  5058.6 1746.75
  5154.8 1748.42  5187.0 1749.53  5192.3 1750.07  5219.2 1750.48  5233.2 1751.30
  5327.6 1753.37  5353.3 1754.29  5359.1 1754.12  5422.9 1756.60  5449.3 1756.82
#Mann=7,-1,0
  4595.1   0.035       0  4635.7    0.07       0  4838.5   0.035       0
  4901.0    0.07       0  4996.5    0.07       0  5000.5    0.07       0
  5028.5   0.035       0
Bank Sta=4996.5,5000.5
Exp/Cntr=0.3,0.1

Type RM Length L Ch R = 1,21847,446,446,446
BEGIN DESCRIPTION:
Mapping XS 50be64b2
END DESCRIPTION:
XS GIS Cut Line= 3
      1665904.32      6970121.46      1666227.68      6970518.61
      1666480.77      6970817.12
#Sta/Elev= 30
  4490.5 1762.20  4595.1 1762.86  4649.3 1761.06  4666.6 1760.60  4702.1 1757.27
  4722.9 1756.17  4751.6 1751.69  4766.0 1750.67  4772.5 1750.88  4794.7 1749.20
  4801.2 1749.78  4815.6 1747.86  4822.0 1748.20  4858.7 1746.81  4865.1 1747.40
  4879.5 1745.97  4885.9 1746.49  4908.2 1745.45  4915.7 1745.87  4982.8 1743.23
  5005.3 1740.33  5005.6 1739.83  5009.3 1740.33  5036.5 1741.41  5050.2 1742.37
  5191.9 1746.60  5277.2 1750.26  5347.8 1754.23  5393.9 1755.51  5394.0 1755.51
#Mann=8,-1,0
  4490.5   0.035       0  4649.3    0.07       0  4915.7   0.035       0
  4982.8    0.07       0  5005.3    0.07       0  5009.3    0.07       0
  5036.5   0.035       0  5393.9    0.07       0
Bank Sta=5005.3,5009.3
Exp/Cntr=0.3,0.1

Type RM Length L Ch R = 1,21401,431,431,431
BEGIN DESCRIPTION:
Mapping XS ef6eeee9
END DESCRIPTION:
XS GIS Cut Line= 3
      1665695.55      6970226.92      1665848.34      6970497.78
      1666028.30      6970804.04
#Sta/Elev= 30
  4690.8 1757.67  4715.3 1756.64  4763.8 1754.76  4779.7 1753.58  4785.5 1754.27
  4801.4 1753.63  4807.1 1754.45  4826.5 1754.82  4844.7 1754.81  4866.3 1753.42
  4875.7 1752.16  4882.3 1750.06  4903.9 1747.83  4919.8 1745.36  4925.6 1743.84
  4941.5 1741.89  4984.8 1738.15  4990.6 1737.08  5004.4 1736.58  5004.7 1736.08
  5008.2 1736.08  5008.4 1736.58  5008.8 1736.61  5049.4 1739.16  5094.8 1739.96
  5168.3 1743.01  5182.3 1743.44  5203.7 1745.36  5292.0 1749.25  5357.0 1749.88
#Mann=7,-1,0
  4690.8    0.07       0  4715.3   0.035       0  4826.5    0.07       0
  5004.4    0.07       0  5008.4    0.07       0  5008.8   0.035       0
  5168.3    0.07       0
Bank Sta=5004.4,5008.4
Exp/Cntr=0.3,0.1

Type RM Length L Ch R = 1,20970,332,332,332
BEGIN DESCRIPTION:
Mapping XS a383cdfb
END DESCRIPTION:
XS GIS Cut Line= 3
      1665546.27      6970376.27      1665674.73      6970872.78
      1665817.08      6971317.18
#Sta/Elev= 30
  4490.3 1755.49  4551.6 1753.88  4574.7 1752.98  4636.7 1748.17  4692.3 1746.51
  4739.8 1744.78  4779.2 1742.19  4908.7 1735.52  4936.2 1735.16  4956.9 1731.14
  4975.5 1730.62  4975.7 1730.12  4979.4 1730.12  4979.7 1730.62  4983.5 1731.09
  4988.7 1733.19  4998.1 1734.67  5022.4 1736.23  5054.6 1735.90  5061.1 1734.86
  5081.4 1735.66  5145.1 1738.94  5151.0 1740.00  5156.2 1739.81  5176.6 1741.34
  5183.1 1742.50  5215.3 1744.52  5284.8 1747.84  5343.8 1752.69  5469.8 1757.26
#Mann=7,-1,0
  4490.3   0.035       0  4551.6    0.07       0  4692.3   0.035       0
  4779.2    0.07       0  4908.7   0.035       0  4975.5   0.035       0
  4979.7   0.035       0
Bank Sta=4975.5,4979.7
Exp/Cntr=0.3,0.1

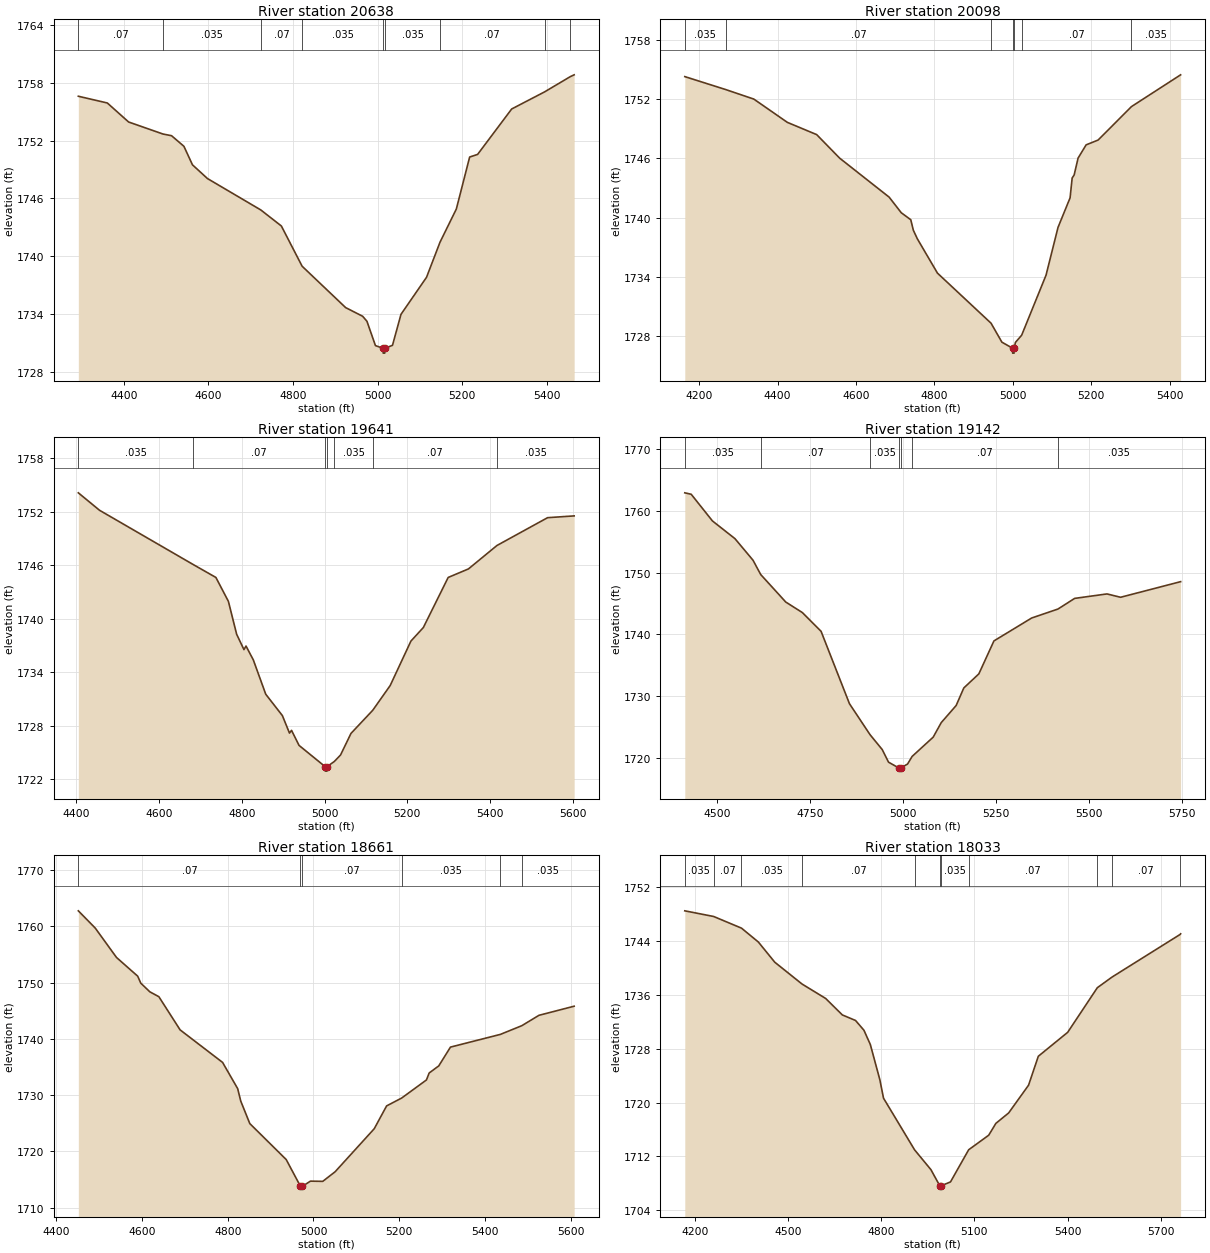
Type RM Length L Ch R = 1,20638,540,540,540
BEGIN DESCRIPTION:
Mapping XS bdcb4119
END DESCRIPTION:
XS GIS Cut Line= 3
      1665325.78      6970339.83      1665405.64      6971048.13
      1665459.25      6971504.71
#Sta/Elev= 30
  4292.4 1756.60  4361.0 1755.90  4411.3 1753.93  4492.8 1752.68  4512.8 1752.51
  4542.1 1751.41  4562.3 1749.49  4597.7 1748.07  4724.0 1744.81  4772.5 1743.15
  4821.6 1738.98  4924.5 1734.69  4964.8 1733.79  4974.9 1733.27  4995.0 1730.75
  5013.0 1730.47  5013.3 1729.97  5017.0 1729.97  5017.3 1730.47  5035.3 1730.78
  5055.4 1733.99  5115.8 1737.83  5147.7 1741.47  5186.3 1744.91  5217.8 1750.30
  5236.6 1750.57  5317.2 1755.28  5394.9 1757.05  5455.7 1758.63  5464.9 1758.82
#Mann=9,-1,0
  4292.4    0.07       0  4492.8   0.035       0  4724.0    0.07       0
  4821.6   0.035       0  5013.0   0.035       0  5017.3   0.035       0
  5147.7    0.07       0  5394.9   0.035       0  5455.7    0.07       0
Bank Sta=5013,5017.3
Exp/Cntr=0.3,0.1

Type RM Length L Ch R = 1,20098,457,457,457
BEGIN DESCRIPTION:
Mapping XS 2ed5f5bb
END DESCRIPTION:
XS GIS Cut Line= 3
      1665099.38      6970270.39      1664909.28      6971093.26
      1664823.53      6971503.86
#Sta/Elev= 30
  4163.6 1754.29  4267.6 1752.98  4339.6 1752.01  4425.1 1749.65  4499.8 1748.41
  4558.5 1746.02  4684.6 1742.07  4715.4 1740.49  4739.7 1739.78  4746.2 1738.72
  4756.4 1737.85  4807.7 1734.37  4944.4 1729.29  4972.0 1727.37  4999.1 1726.76
  4999.4 1726.26  5003.1 1726.26  5003.4 1726.76  5006.4 1727.34  5022.4 1728.08
  5084.5 1734.16  5115.1 1739.01  5145.8 1742.00  5151.1 1744.01  5156.2 1744.32
  5166.2 1746.03  5186.7 1747.37  5217.3 1747.86  5302.3 1751.25  5427.6 1754.47
#Mann=7,-1,0
  4163.6   0.035       0  4267.6    0.07       0  4944.4   0.035       0
  4999.1   0.035       0  5003.4   0.035       0  5022.4    0.07       0
  5302.3   0.035       0
Bank Sta=4999.1,5003.4
Exp/Cntr=0.3,0.1

Type RM Length L Ch R = 1,19641,499,499,499
BEGIN DESCRIPTION:
Mapping XS 628d81e1
END DESCRIPTION:
XS GIS Cut Line= 3
      1664596.78      6970246.95      1664542.09      6970843.26
      1664521.26      6971442.19
#Sta/Elev= 30
  4405.1 1754.14  4456.4 1752.18  4681.6 1746.12  4737.5 1744.64  4767.7 1741.96
  4787.7 1738.26  4805.3 1736.54  4810.3 1736.94  4827.9 1735.39  4858.0 1731.53
  4898.2 1729.13  4915.3 1727.17  4920.3 1727.48  4938.4 1725.79  5001.6 1723.40
  5001.9 1722.90  5005.7 1722.90  5006.0 1723.40  5023.6 1723.98  5038.7 1724.71
  5063.9 1727.13  5116.5 1729.73  5158.7 1732.51  5208.8 1737.50  5238.8 1739.02
  5298.8 1744.64  5347.8 1745.60  5416.7 1748.23  5539.0 1751.35  5603.2 1751.55
#Mann=7,-1,0
  4405.1   0.035       0  4681.6    0.07       0  5001.6    0.07       0
  5006.0    0.07       0  5023.6   0.035       0  5116.5    0.07       0
  5416.7   0.035       0
Bank Sta=5001.6,5006
Exp/Cntr=0.3,0.1

Type RM Length L Ch R = 1,19142,481,481,481
BEGIN DESCRIPTION:
Mapping XS 1992d73d
END DESCRIPTION:
XS GIS Cut Line= 3
      1664028.20      6970304.16      1664097.65      6970894.48
      1664215.65      6971623.30
#Sta/Elev= 30
  4414.2 1762.88  4431.4 1762.65  4488.5 1758.34  4549.0 1755.48  4597.5 1752.00
  4618.3 1749.68  4685.6 1745.24  4730.2 1743.54  4780.5 1740.51  4856.8 1728.82
  4912.2 1723.81  4944.9 1721.41  4961.8 1719.38  4989.7 1718.43  4990.1 1717.93
  4994.2 1718.43  5012.9 1719.07  5025.3 1720.31  5081.9 1723.42  5103.3 1725.75
  5143.6 1728.53  5164.1 1731.36  5204.6 1733.64  5245.1 1738.96  5346.5 1742.66
  5417.2 1744.11  5462.1 1745.83  5549.1 1746.55  5585.5 1746.01  5746.9 1748.53
#Mann=7,-1,0
  4414.2   0.035       0  4618.3    0.07       0  4912.2   0.035       0
  4989.7   0.035       0  4994.2   0.035       0  5025.3    0.07       0
  5417.2   0.035       0
Bank Sta=4989.7,4994.2
Exp/Cntr=0.3,0.1

Type RM Length L Ch R = 1,18661,628,628,628
BEGIN DESCRIPTION:
Mapping XS 8d05d964
END DESCRIPTION:
XS GIS Cut Line= 3
      1663344.20      6970772.98      1663722.65      6971165.31
      1664103.98      6971643.71
#Sta/Elev= 30
  4451.3 1762.76  4490.7 1759.70  4540.4 1754.47  4589.8 1751.15  4597.0 1749.91
  4618.1 1748.37  4639.2 1747.50  4688.8 1741.60  4787.9 1735.82  4823.1 1731.16
  4830.3 1728.94  4851.4 1724.95  4936.3 1718.56  4969.6 1713.80  4969.9 1713.30
  4974.1 1713.80  4992.9 1714.72  5021.6 1714.68  5050.5 1716.39  5141.7 1724.03
  5170.6 1728.09  5205.8 1729.49  5263.5 1732.70  5269.9 1733.94  5292.3 1735.20
  5319.6 1738.54  5436.1 1740.80  5485.9 1742.34  5526.1 1744.19  5608.2 1745.81
#Mann=6,-1,0
  4451.3    0.07       0  4969.6    0.07       0  4974.1    0.07       0
  5205.8   0.035       0  5436.1    0.07       0  5485.9   0.035       0
Bank Sta=4969.6,4974.1
Exp/Cntr=0.3,0.1

Type RM Length L Ch R = 1,18033,387,387,387
BEGIN DESCRIPTION:
Mapping XS c1f068fb
END DESCRIPTION:
XS GIS Cut Line= 3
      1662483.62      6971408.07      1663299.62      6971599.05
      1664020.97      6971831.41
#Sta/Elev= 30
  4168.0 1748.45  4260.9 1747.61  4350.5 1745.88  4404.8 1743.82  4457.5 1740.83
  4545.6 1737.58  4621.3 1735.45  4675.1 1733.00  4717.5 1732.18  4744.6 1730.73
  4765.2 1728.61  4795.9 1723.37  4807.6 1720.65  4907.6 1712.98  4960.2 1710.04
  4988.7 1707.65  4989.0 1707.15  4993.3 1707.65  5023.2 1708.22  5081.7 1712.99
  5146.2 1715.15  5169.3 1716.91  5210.3 1718.45  5274.4 1722.57  5305.9 1726.87
  5400.4 1730.42  5495.8 1737.04  5543.5 1738.63  5762.4 1744.95  5763.9 1745.04
#Mann=11,-1,0
  4168.0   0.035       0  4260.9    0.07       0  4350.5   0.035       0
  4545.6    0.07       0  4907.6   0.035       0  4988.7   0.035       0
  4993.3   0.035       0  5081.7    0.07       0  5495.8   0.035       0
  5543.5    0.07       0  5762.4   0.035       0
Bank Sta=4988.7,4993.3
Exp/Cntr=0.3,0.1

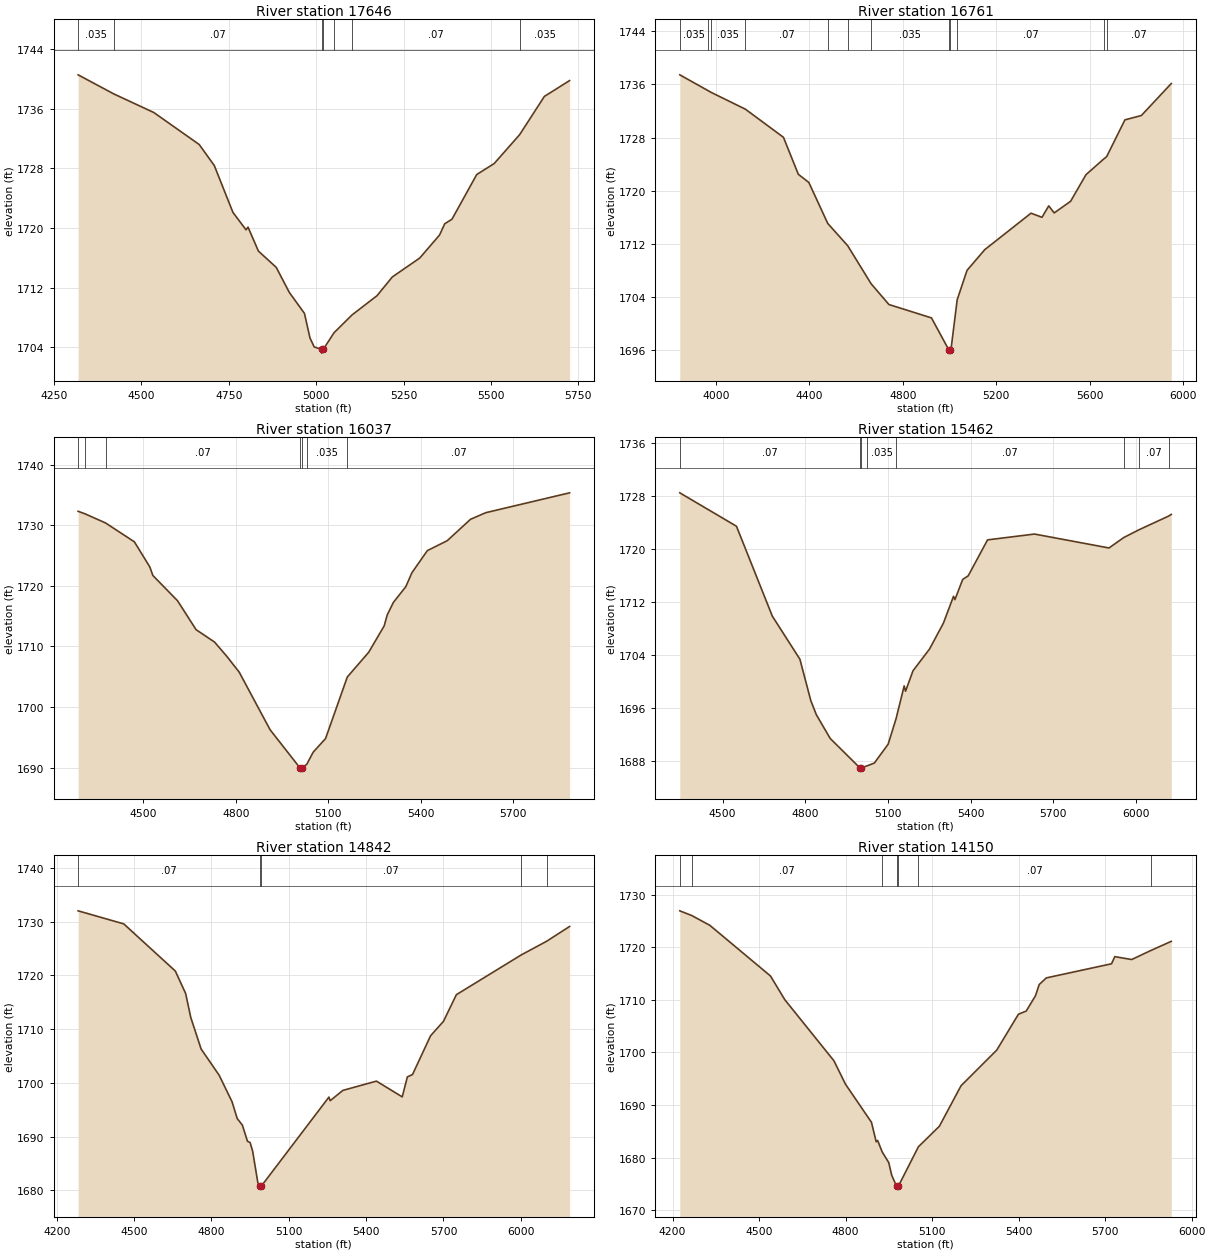
Type RM Length L Ch R = 1,17646,885,885,885
BEGIN DESCRIPTION:
Mapping XS e50fed0e
END DESCRIPTION:
XS GIS Cut Line= 3
      1662566.97      6971602.52      1663157.26      6971939.33
      1663737.11      6972376.82
#Sta/Elev= 30
  4318.7 1740.55  4420.8 1737.99  4535.2 1735.50  4665.1 1731.21  4708.3 1728.39
  4761.6 1722.11  4799.1 1719.77  4804.8 1720.13  4834.5 1716.92  4885.5 1714.74
  4922.9 1711.38  4966.2 1708.57  4982.0 1705.28  4994.1 1704.07  5015.3 1703.74
  5015.6 1703.24  5019.9 1703.74  5051.0 1705.98  5102.3 1708.36  5173.8 1710.94
  5217.5 1713.45  5296.1 1715.99  5352.8 1719.08  5367.4 1720.58  5388.2 1721.19
  5459.0 1727.18  5509.1 1728.66  5582.0 1732.54  5652.5 1737.65  5724.7 1739.78
#Mann=7,-1,0
  4318.7   0.035       0  4420.8    0.07       0  5015.3    0.07       0
  5019.9    0.07       0  5051.0   0.035       0  5102.3    0.07       0
  5582.0   0.035       0
Bank Sta=5015.3,5019.9
Exp/Cntr=0.3,0.1

Type RM Length L Ch R = 1,16761,724,724,724
BEGIN DESCRIPTION:
Mapping XS 4cbf6563
END DESCRIPTION:
XS GIS Cut Line= 3
      1662490.60      6971689.35      1662941.98      6972755.30
      1663320.15      6973622.66
#Sta/Elev= 30
  3845.1 1737.45  3966.7 1735.06  3980.4 1734.79  4126.1 1732.28  4288.9 1728.05
  4352.5 1722.49  4397.5 1721.26  4478.4 1715.10  4563.6 1711.76  4664.2 1706.02
  4740.4 1702.90  4922.4 1700.89  4996.6 1696.09  4996.9 1695.59  5001.3 1696.09
  5006.9 1696.39  5032.5 1703.62  5074.7 1708.04  5150.4 1711.15  5348.6 1716.64
  5395.5 1716.02  5424.4 1717.74  5447.8 1716.68  5518.0 1718.43  5583.8 1722.43
  5659.9 1724.79  5672.3 1725.14  5750.6 1730.68  5820.9 1731.33  5948.9 1736.14
#Mann=12,-1,0
  3845.1   0.035       0  3966.7    0.07       0  3980.4   0.035       0
  4126.1    0.07       0  4478.4   0.035       0  4563.6    0.07       0
  4664.2   0.035       0  4996.6   0.035       0  5001.3   0.035       0
  5032.5    0.07       0  5659.9   0.035       0  5672.3    0.07       0
Bank Sta=4996.6,5001.3
Exp/Cntr=0.3,0.1

Type RM Length L Ch R = 1,16037,575,575,575
BEGIN DESCRIPTION:
Mapping XS 86e3ea76
END DESCRIPTION:
XS GIS Cut Line= 3
      1662311.42      6971835.48      1662311.42      6972549.05
      1662327.05      6973429.24
#Sta/Elev= 30
  4288.7 1732.32  4310.8 1731.91  4377.6 1730.40  4471.2 1727.28  4521.2 1723.14
  4531.2 1721.72  4611.2 1717.55  4671.2 1712.78  4731.2 1710.73  4771.2 1708.36
  4811.2 1705.76  4911.2 1696.26  5008.8 1689.92  5009.1 1689.42  5013.7 1689.92
  5030.1 1690.54  5051.2 1692.56  5091.2 1694.80  5161.7 1704.96  5231.3 1709.06
  5281.3 1713.40  5291.3 1715.23  5311.3 1717.29  5351.3 1719.86  5371.3 1722.18
  5421.3 1725.83  5485.9 1727.47  5561.3 1731.00  5611.3 1732.10  5882.6 1735.37
#Mann=7,-1,0
  4288.7    0.07       0  4310.8   0.035       0  4377.6    0.07       0
  5008.8    0.07       0  5013.7    0.07       0  5030.1   0.035       0
  5161.7    0.07       0
Bank Sta=5008.8,5013.7
Exp/Cntr=0.3,0.1

Type RM Length L Ch R = 1,15462,620,620,620
BEGIN DESCRIPTION:
Mapping XS 1c436c79
END DESCRIPTION:
XS GIS Cut Line= 3
      1661827.05      6971632.42      1661821.84      6972304.26
      1661884.32      6973413.34
#Sta/Elev= 30
  4344.8 1728.52  4550.4 1723.48  4680.4 1709.92  4780.4 1703.42  4820.4 1697.12
  4840.4 1695.02  4890.4 1691.46  4997.9 1687.03  4998.3 1686.53  5002.9 1687.03
  5024.0 1687.32  5050.5 1687.75  5100.5 1690.59  5129.2 1694.43  5158.7 1699.39
  5163.7 1698.59  5190.7 1701.67  5250.8 1704.96  5300.9 1708.85  5337.7 1712.91
  5342.7 1712.40  5371.0 1715.45  5391.0 1716.00  5461.1 1721.42  5631.4 1722.30
  5901.8 1720.20  5955.0 1721.77  6010.1 1722.94  6117.8 1725.01  6127.5 1725.26
#Mann=8,-1,0
  4344.8    0.07       0  4997.9    0.07       0  5002.9    0.07       0
  5024.0   0.035       0  5129.2    0.07       0  5955.0   0.035       0
  6010.1    0.07       0  6117.8   0.035       0
Bank Sta=4997.9,5002.9
Exp/Cntr=0.3,0.1

Type RM Length L Ch R = 1,14842,692,692,692
BEGIN DESCRIPTION:
Mapping XS 53be812a
END DESCRIPTION:
XS GIS Cut Line= 3
      1661233.30      6971470.89      1661233.30      6972194.89
      1661217.67      6973377.18
#Sta/Elev= 30
  4282.9 1731.99  4460.0 1729.56  4660.0 1720.79  4700.0 1716.61  4720.0 1712.14
  4760.0 1706.29  4830.0 1701.41  4880.0 1696.48  4900.0 1693.36  4920.0 1692.13
  4940.0 1689.11  4950.0 1688.90  4960.0 1687.27  4980.0 1681.44  4987.5 1680.72
  4987.9 1680.22  4992.6 1680.72  5255.8 1697.34  5260.8 1696.67  5310.0 1698.59
  5440.1 1700.31  5540.1 1697.38  5560.1 1701.10  5580.1 1701.54  5650.1 1708.75
  5700.1 1711.43  5750.1 1716.39  6002.2 1723.80  6100.0 1726.32  6189.3 1729.08
#Mann=5,-1,0
  4282.9    0.07       0  4987.5    0.07       0  4992.6    0.07       0
  6002.2   0.035       0  6100.0    0.07       0
Bank Sta=4987.5,4992.6
Exp/Cntr=0.3,0.1

Type RM Length L Ch R = 1,14150,583,583,583
BEGIN DESCRIPTION:
Mapping XS 19e50bd9
END DESCRIPTION:
XS GIS Cut Line= 3
      1660543.63      6971513.94      1660574.01      6972299.49
      1660851.27      6973174.58
#Sta/Elev= 30
  4225.2 1726.92  4266.5 1726.03  4329.3 1724.17  4539.5 1714.54  4589.5 1710.01
  4759.7 1698.41  4799.7 1693.96  4889.8 1686.72  4906.2 1683.01  4911.2 1683.27
  4926.8 1681.10  4949.8 1679.05  4959.8 1676.68  4977.2 1674.51  4977.6 1674.01
  4982.5 1674.51  5052.6 1682.07  5125.2 1685.96  5200.3 1693.66  5324.2 1700.44
  5399.3 1707.26  5426.3 1707.86  5458.6 1710.78  5471.3 1712.90  5496.1 1714.17
  5722.1 1716.85  5733.6 1718.21  5792.0 1717.66  5857.4 1719.35  5929.3 1721.12
#Mann=7,-1,0
  4225.2   0.035       0  4266.5    0.07       0  4926.8   0.035       0
  4977.2   0.035       0  4982.5   0.035       0  5052.6    0.07       0
  5857.4   0.035       0
Bank Sta=4977.2,4982.5
Exp/Cntr=0.3,0.1

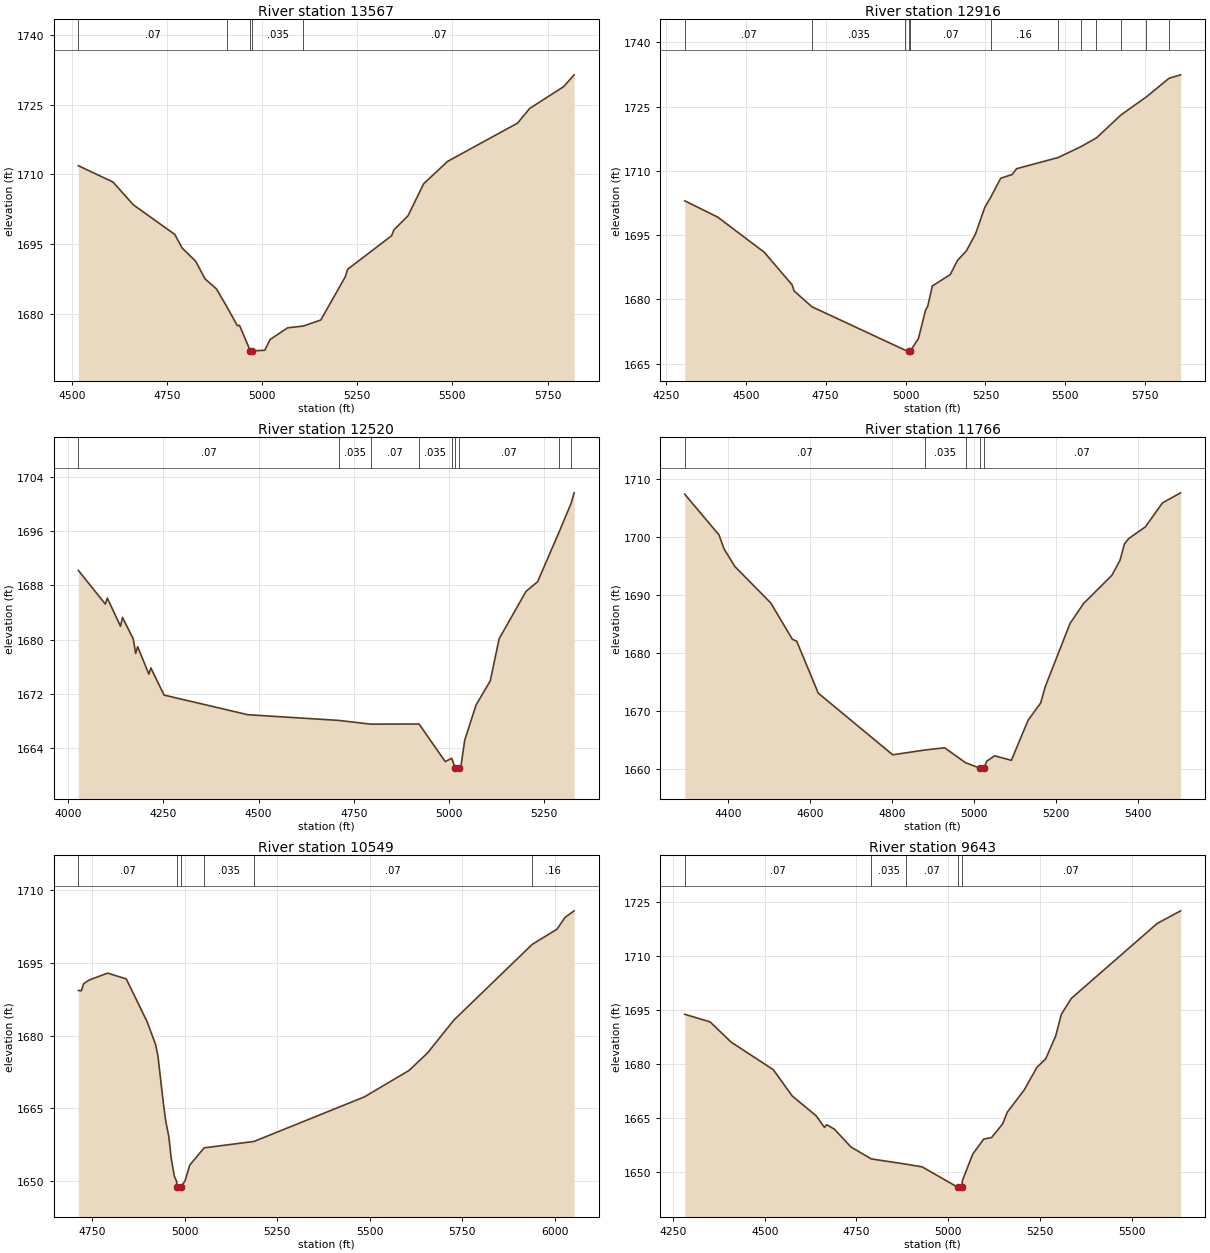
Type RM Length L Ch R = 1,13567,651,651,651
BEGIN DESCRIPTION:
Mapping XS 855ed670
END DESCRIPTION:
XS GIS Cut Line= 3
      1660179.06      6971782.96      1660005.43      6972238.72
      1659754.12      6973014.31
#Sta/Elev= 30
  4517.0 1711.87  4608.0 1708.36  4661.5 1703.46  4770.5 1697.09  4789.9 1694.16
  4825.4 1691.32  4850.1 1687.52  4880.2 1685.35  4906.7 1681.62  4935.0 1677.45
  4940.4 1677.56  4969.0 1672.06  4969.5 1671.56  4974.6 1672.06  5007.0 1672.17
  5021.0 1674.49  5067.0 1677.00  5108.7 1677.39  5154.2 1678.69  5218.2 1687.93
  5224.7 1689.59  5340.3 1696.81  5346.2 1698.05  5383.4 1701.10  5424.4 1707.97
  5487.5 1712.80  5671.3 1721.03  5703.3 1724.19  5792.3 1728.86  5820.0 1731.41
#Mann=5,-1,0
  4517.0    0.07       0  4906.7   0.035       0  4969.0   0.035       0
  4974.6   0.035       0  5108.7    0.07       0
Bank Sta=4969,4974.6
Exp/Cntr=0.3,0.1

Type RM Length L Ch R = 1,12916,396,396,396
BEGIN DESCRIPTION:
Mapping XS aa00a389
END DESCRIPTION:
XS GIS Cut Line= 3
      1660074.92      6971904.51      1659393.45      6972091.15
      1658720.93      6972603.14
#Sta/Elev= 30
  4309.1 1703.02  4412.2 1699.21  4557.9 1691.01  4645.0 1683.40  4651.2 1681.97
  4706.8 1678.29  4999.4 1668.13  5009.4 1667.96  5009.9 1667.46  5015.2 1667.96
  5040.2 1670.86  5063.0 1677.58  5069.3 1678.37  5083.8 1683.13  5140.0 1685.81
  5162.8 1689.14  5189.9 1691.29  5219.0 1695.28  5248.0 1701.48  5266.0 1703.78
  5297.9 1708.29  5333.3 1709.15  5347.8 1710.52  5477.5 1713.12  5547.8 1715.62
  5597.3 1717.70  5674.9 1723.11  5753.4 1727.26  5824.8 1731.63  5860.9 1732.43
#Mann=12,-1,0
  4309.1    0.07       0  4706.8   0.035       0  4999.4    0.07       0
  5009.4    0.07       0  5015.2    0.07       0  5266.0    0.16       0
  5477.5    0.07       0  5547.8   0.035       0  5597.3    0.07       0
  5674.9   0.035       0  5753.4    0.07       0  5824.8   0.035       0
Bank Sta=5009.4,5015.2
Exp/Cntr=0.3,0.1

Type RM Length L Ch R = 1,12520,754,754,754
BEGIN DESCRIPTION:
Mapping XS ebb14158
END DESCRIPTION:
XS GIS Cut Line= 3
      1658970.27      6970898.93      1659225.05      6971837.88
      1659180.00      6972162.98
#Sta/Elev= 30
  4027.1 1690.18  4098.0 1685.22  4103.1 1686.11  4137.8 1681.95  4143.0 1683.26
  4171.2 1680.09  4177.6 1677.95  4182.8 1678.95  4212.2 1674.90  4217.4 1675.82
  4252.0 1671.82  4471.7 1668.93  4710.2 1668.09  4794.1 1667.54  4921.2 1667.56
  4989.8 1662.03  5006.9 1662.51  5015.8 1661.12  5016.3 1660.62  5024.9 1661.12
  5030.4 1661.12  5041.2 1665.22  5070.8 1670.36  5107.9 1673.89  5131.4 1680.12
  5202.0 1687.10  5232.3 1688.51  5289.4 1695.92  5320.2 1700.06  5328.2 1701.60
#Mann=9,-1,0
  4027.1    0.07       0  4710.2   0.035       0  4794.1    0.07       0
  4921.2   0.035       0  5006.9    0.07       0  5015.8   0.035       0
  5024.9    0.07       0  5289.4    0.16       0  5320.2    0.07       0
Bank Sta=5015.8,5024.9
Exp/Cntr=0.3,0.1

Type RM Length L Ch R = 1,11766,1217,1217,1217
BEGIN DESCRIPTION:
Mapping XS ccadf178
END DESCRIPTION:
XS GIS Cut Line= 3
      1658939.05      6970628.61      1658713.34      6971309.21
      1658609.84      6971792.19
#Sta/Elev= 30
  4293.8 1707.44  4377.4 1700.43  4389.7 1698.02  4416.1 1694.98  4503.9 1688.68
  4556.5 1682.43  4567.1 1682.10  4619.8 1673.13  4801.6 1662.50  4880.9 1663.33
  4928.4 1663.71  4979.8 1661.12  5015.2 1660.18  5015.7 1659.68  5024.4 1660.18
  5031.0 1661.37  5050.5 1662.33  5091.4 1661.54  5132.3 1668.46  5163.0 1671.44
  5174.2 1674.26  5234.6 1685.14  5267.9 1688.61  5336.9 1693.46  5356.5 1696.00
  5367.6 1698.87  5377.8 1699.79  5418.7 1701.82  5460.5 1705.96  5504.8 1707.69
#Mann=5,-1,0
  4293.8    0.07       0  4880.9   0.035       0  4979.8    0.07       0
  5015.2    0.07       0  5024.4    0.07       0
Bank Sta=5015.2,5024.4
Exp/Cntr=0.3,0.1

Type RM Length L Ch R = 1,10549,906,906,906
BEGIN DESCRIPTION:
Mapping XS b5f9f262
END DESCRIPTION:
XS GIS Cut Line= 3
      1657584.88      6970757.14      1657814.03      6970923.79
      1658449.45      6971767.54
#Sta/Elev= 30
  4713.0 1689.31  4721.1 1689.24  4727.3 1690.70  4742.0 1691.45  4792.2 1692.89
  4842.5 1691.69  4898.9 1682.85  4922.1 1678.07  4928.3 1675.66  4942.9 1665.93
  4949.1 1662.39  4957.6 1659.12  4963.8 1654.77  4972.3 1650.99  4978.5 1649.91
  4979.9 1648.81  4980.4 1648.31  4990.4 1648.81  5001.3 1650.01  5014.1 1653.28
  5052.9 1656.83  5187.7 1658.15  5486.0 1667.35  5606.7 1672.81  5656.7 1676.43
  5727.7 1683.20  5939.2 1698.81  6006.5 1701.97  6028.1 1704.40  6052.6 1705.74
#Mann=6,-1,0
  4713.0    0.07       0  4979.9    0.07       0  4990.4    0.07       0
  5052.9   0.035       0  5187.7    0.07       0  5939.2    0.16       0
Bank Sta=4979.9,4990.4
Exp/Cntr=0.3,0.1

Type RM Length L Ch R = 1,9643,847,847,847
BEGIN DESCRIPTION:
Mapping XS 27eae424
END DESCRIPTION:
XS GIS Cut Line= 3
      1657588.34      6970836.98      1657195.98      6971448.10
      1656873.06      6971982.83
#Sta/Elev= 30
  4282.3 1693.83  4351.1 1691.73  4408.5 1686.10  4523.5 1678.40  4575.0 1671.09
  4640.0 1665.59  4662.9 1662.35  4668.8 1663.10  4690.0 1661.84  4735.1 1656.88
  4790.6 1653.56  4883.9 1652.12  4929.1 1651.35  5026.4 1645.65  5026.9 1645.15
  5037.2 1645.65  5038.5 1647.50  5066.8 1654.90  5096.8 1659.10  5118.1 1659.50
  5148.6 1663.36  5160.8 1666.56  5207.0 1672.76  5242.1 1679.13  5265.4 1681.40
  5292.8 1687.78  5308.3 1693.86  5335.5 1698.27  5569.2 1719.12  5633.2 1722.65
#Mann=5,-1,0
  4282.3    0.07       0  4790.6   0.035       0  4883.9    0.07       0
  5026.4    0.07       0  5037.2    0.07       0
Bank Sta=5026.4,5037.2
Exp/Cntr=0.3,0.1

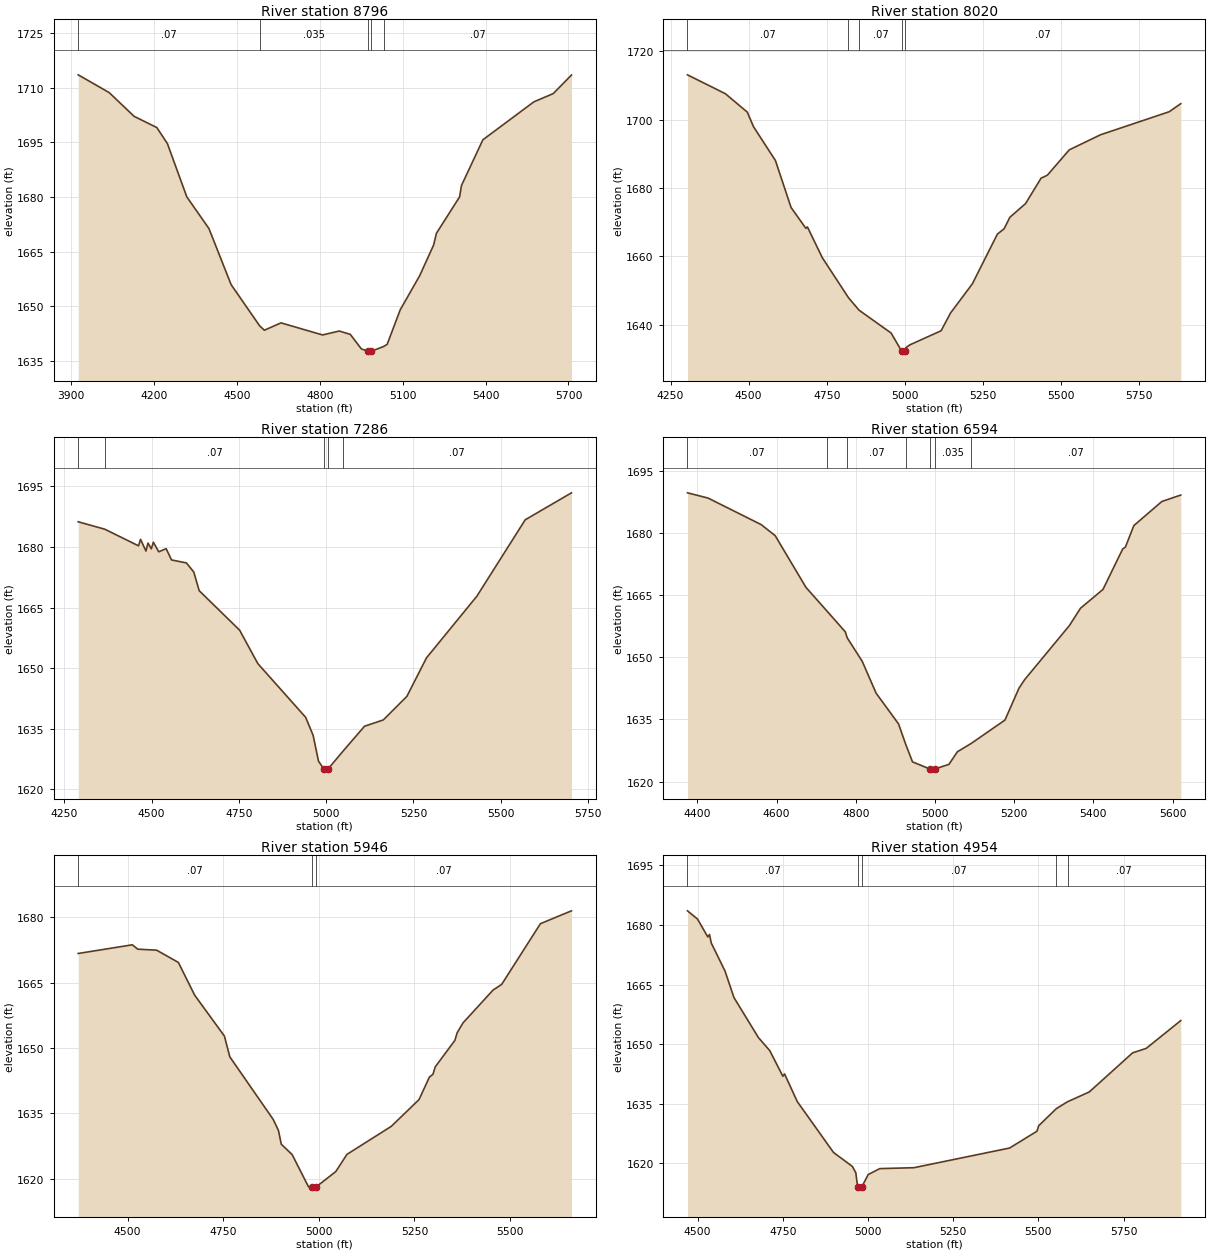
Type RM Length L Ch R = 1,8796,776,776,776
BEGIN DESCRIPTION:
Mapping XS 83370d96
END DESCRIPTION:
XS GIS Cut Line= 3
      1656629.77      6969866.18      1656553.39      6970949.49
      1656473.58      6971643.42
#Sta/Elev= 30
  3926.3 1713.52  4038.4 1708.64  4128.6 1702.12  4210.6 1699.05  4248.9 1694.66
  4319.1 1680.02  4399.3 1671.30  4479.5 1655.91  4582.9 1644.58  4599.8 1643.39
  4659.9 1645.41  4810.3 1642.09  4870.5 1643.17  4910.6 1642.25  4950.7 1638.26
  4975.3 1637.60  4975.8 1637.10  4986.2 1637.60  5031.3 1638.93  5044.0 1639.51
  5091.3 1649.00  5161.8 1658.38  5212.0 1666.77  5222.2 1670.00  5306.1 1680.01
  5312.8 1683.12  5390.2 1695.67  5574.5 1706.09  5644.9 1708.37  5710.8 1713.46
#Mann=5,-1,0
  3926.3    0.07       0  4582.9   0.035       0  4975.3   0.035       0
  4986.2   0.035       0  5031.3    0.07       0
Bank Sta=4975.3,4986.2
Exp/Cntr=0.3,0.1

Type RM Length L Ch R = 1,8020,734,734,734
BEGIN DESCRIPTION:
Mapping XS d2e584f0
END DESCRIPTION:
XS GIS Cut Line= 3
      1655924.92      6969796.75      1655952.69      6970498.10
      1655973.48      6971374.76
#Sta/Elev= 30
  4304.3 1713.14  4425.6 1707.61  4495.7 1702.23  4515.7 1697.95  4585.8 1688.06
  4635.8 1674.31  4683.2 1668.21  4688.2 1668.61  4735.9 1659.60  4819.6 1647.90
  4853.5 1644.24  4956.1 1637.55  4990.4 1632.17  4990.9 1631.67  5001.7 1632.17
  5003.6 1633.29  5016.1 1634.09  5116.1 1638.22  5146.1 1643.39  5216.2 1651.97
  5296.2 1666.51  5317.8 1668.07  5336.2 1671.44  5386.2 1675.43  5436.2 1682.90
  5456.2 1683.76  5526.2 1691.17  5626.3 1695.59  5846.3 1702.34  5883.1 1704.70
#Mann=5,-1,0
  4304.3    0.07       0  4819.6    0.16       0  4853.5    0.07       0
  4990.4    0.07       0  5001.7    0.07       0
Bank Sta=4990.4,5001.7
Exp/Cntr=0.3,0.1

Type RM Length L Ch R = 1,7286,692,692,692
BEGIN DESCRIPTION:
Mapping XS 077fbcba
END DESCRIPTION:
XS GIS Cut Line= 3
      1654917.99      6969998.14      1655292.97      6970605.74
      1655612.41      6971227.26
#Sta/Elev= 30
  4289.9 1686.24  4366.1 1684.40  4462.6 1680.29  4468.5 1681.89  4483.9 1678.99
  4489.8 1680.97  4499.3 1679.54  4505.2 1681.18  4520.5 1678.81  4541.8 1679.58
  4557.2 1676.79  4599.8 1676.05  4621.0 1673.79  4636.4 1669.18  4752.3 1659.39
  4804.4 1651.12  4941.5 1637.80  4962.8 1633.34  4978.2 1626.94  4993.8 1624.99
  4994.3 1624.49  5005.2 1624.99  5047.5 1629.35  5110.0 1635.61  5163.8 1637.17
  5231.3 1643.01  5287.5 1652.55  5431.5 1667.78  5570.2 1686.73  5702.7 1693.41
#Mann=5,-1,0
  4289.9   0.035       0  4366.1    0.07       0  4993.8   0.035       0
  5005.2    0.07       0  5047.5    0.07       0
Bank Sta=4993.8,5005.2
Exp/Cntr=0.3,0.1

Type RM Length L Ch R = 1,6594,648,648,648
BEGIN DESCRIPTION:
Mapping XS 8fa821eb
END DESCRIPTION:
XS GIS Cut Line= 3
      1654246.10      6970514.07      1654711.37      6970934.21
      1655138.46      6971382.13
#Sta/Elev= 30
  4375.0 1689.67  4426.9 1688.41  4561.4 1681.99  4596.5 1679.34  4674.3 1666.86
  4727.7 1661.11  4773.6 1656.14  4778.4 1654.70  4816.2 1649.06  4851.4 1641.35
  4908.1 1633.93  4925.7 1629.13  4943.3 1624.78  4987.6 1623.04  4988.1 1622.54
  4999.1 1623.04  5035.3 1624.17  5056.7 1627.21  5091.1 1629.19  5176.8 1634.85
  5212.4 1642.58  5226.5 1644.60  5339.4 1657.63  5367.7 1661.84  5424.4 1666.37
  5474.1 1676.11  5481.0 1676.59  5502.4 1681.77  5573.1 1687.58  5620.8 1689.13
#Mann=7,-1,0
  4375.0    0.07       0  4727.7    0.16       0  4778.4    0.07       0
  4925.7   0.035       0  4987.6   0.035       0  4999.1   0.035       0
  5091.1    0.07       0
Bank Sta=4987.6,4999.1
Exp/Cntr=0.3,0.1

Type RM Length L Ch R = 1,5946,992,992,992
BEGIN DESCRIPTION:
Mapping XS c0d32c61
END DESCRIPTION:
XS GIS Cut Line= 3
      1653746.11      6970757.14      1654169.71      6971232.82
      1654718.28      6971586.96
#Sta/Elev= 30
  4370.9 1671.68  4512.4 1673.67  4526.6 1672.67  4575.9 1672.44  4632.8 1669.63
  4675.4 1662.12  4753.2 1652.73  4767.4 1647.95  4880.9 1633.58  4894.5 1631.07
  4902.0 1627.90  4930.4 1625.51  4973.1 1618.13  4981.5 1618.09  4982.0 1617.59
  4993.0 1618.09  5044.5 1621.62  5073.7 1625.57  5189.6 1632.00  5262.2 1638.15
  5289.3 1643.31  5298.5 1643.94  5304.5 1645.65  5355.9 1651.73  5361.9 1653.49
  5377.1 1655.74  5455.6 1663.27  5478.4 1664.60  5579.6 1678.52  5660.8 1681.47
#Mann=3,-1,0
  4370.9    0.07       0  4981.5    0.07       0  4993.0    0.07       0
Bank Sta=4981.5,4993
Exp/Cntr=0.3,0.1

Type RM Length L Ch R = 1,4954,434,434,434
BEGIN DESCRIPTION:
Mapping XS 07155c35
END DESCRIPTION:
XS GIS Cut Line= 3
      1652825.83      6971614.15      1653351.91      6971687.07
      1654265.96      6971624.57
#Sta/Elev= 30
  4470.3 1683.55  4499.8 1681.48  4529.9 1676.98  4534.9 1677.59  4540.1 1675.46
  4580.5 1668.39  4606.7 1661.73  4678.4 1651.67  4711.8 1648.38  4750.2 1641.93
  4755.2 1642.51  4792.5 1635.56  4898.7 1622.77  4954.1 1619.25  4964.2 1617.66
  4969.7 1614.04  4970.2 1613.54  4981.4 1614.04  5000.5 1617.20  5034.6 1618.70
  5134.8 1618.93  5415.5 1623.88  5495.7 1628.11  5500.8 1629.49  5552.5 1633.78
  5585.4 1635.52  5649.3 1637.99  5776.3 1647.82  5816.4 1648.95  5917.6 1655.94
#Mann=5,-1,0
  4470.3    0.07       0  4969.7    0.07       0  4981.4    0.07       0
  5552.5   0.035       0  5585.4    0.07       0
Bank Sta=4969.7,4981.4
Exp/Cntr=0.3,0.1