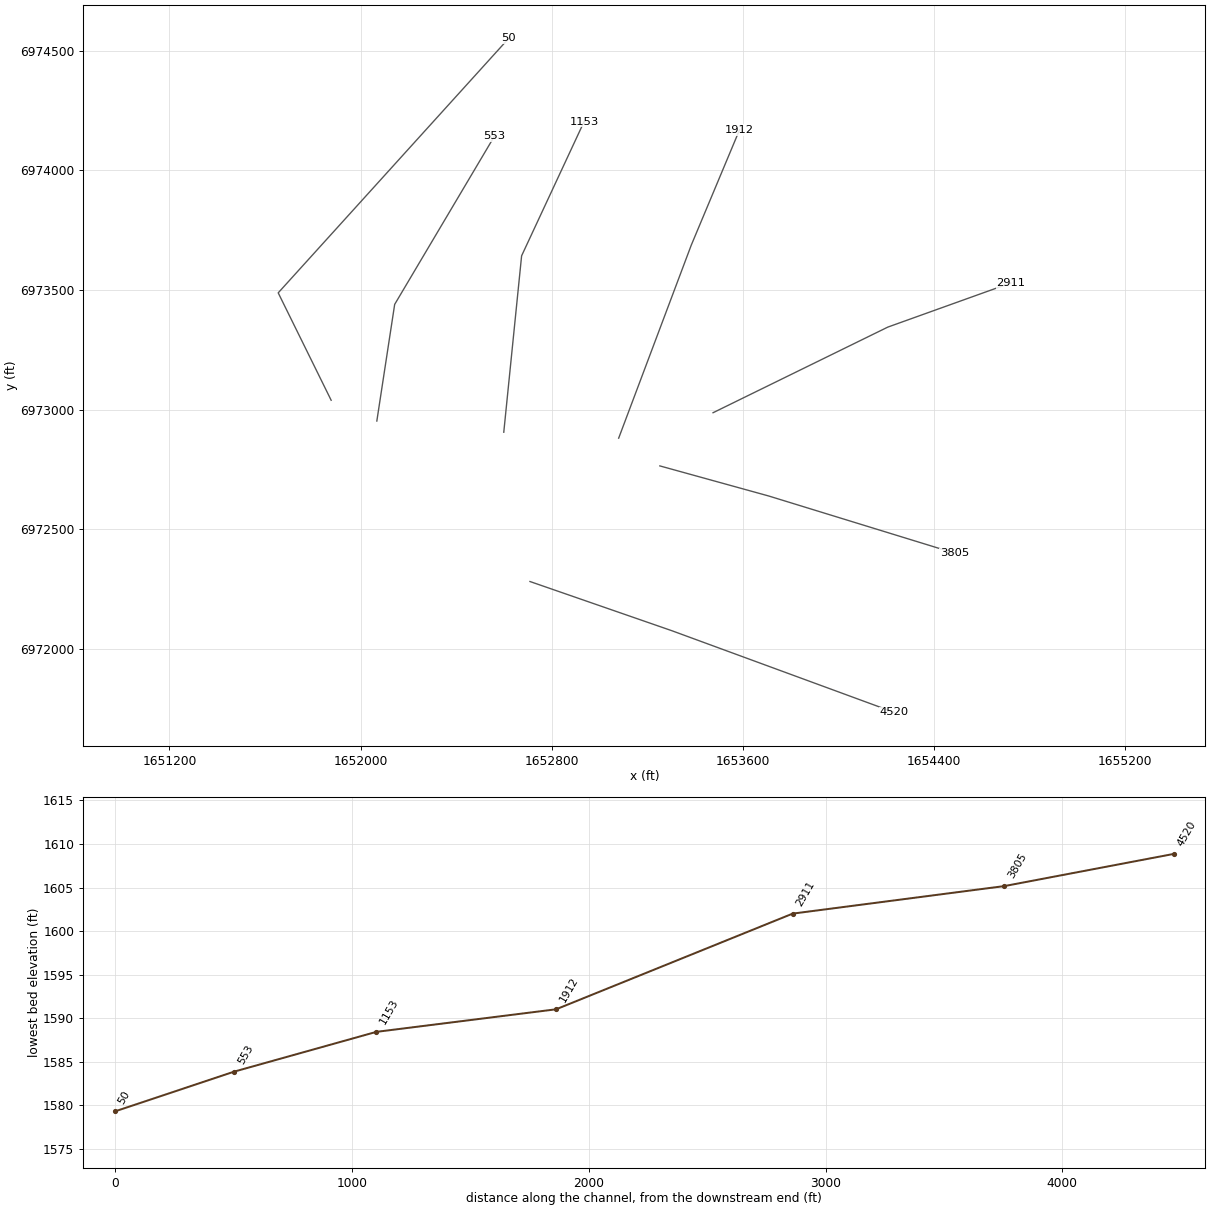
HEC-RAS study Chimney Creek 1144.prj: Chimney Creek 1144 Base Level Engineering

--- Chimney Creek 1144.g01 (geometry) --- (continued)

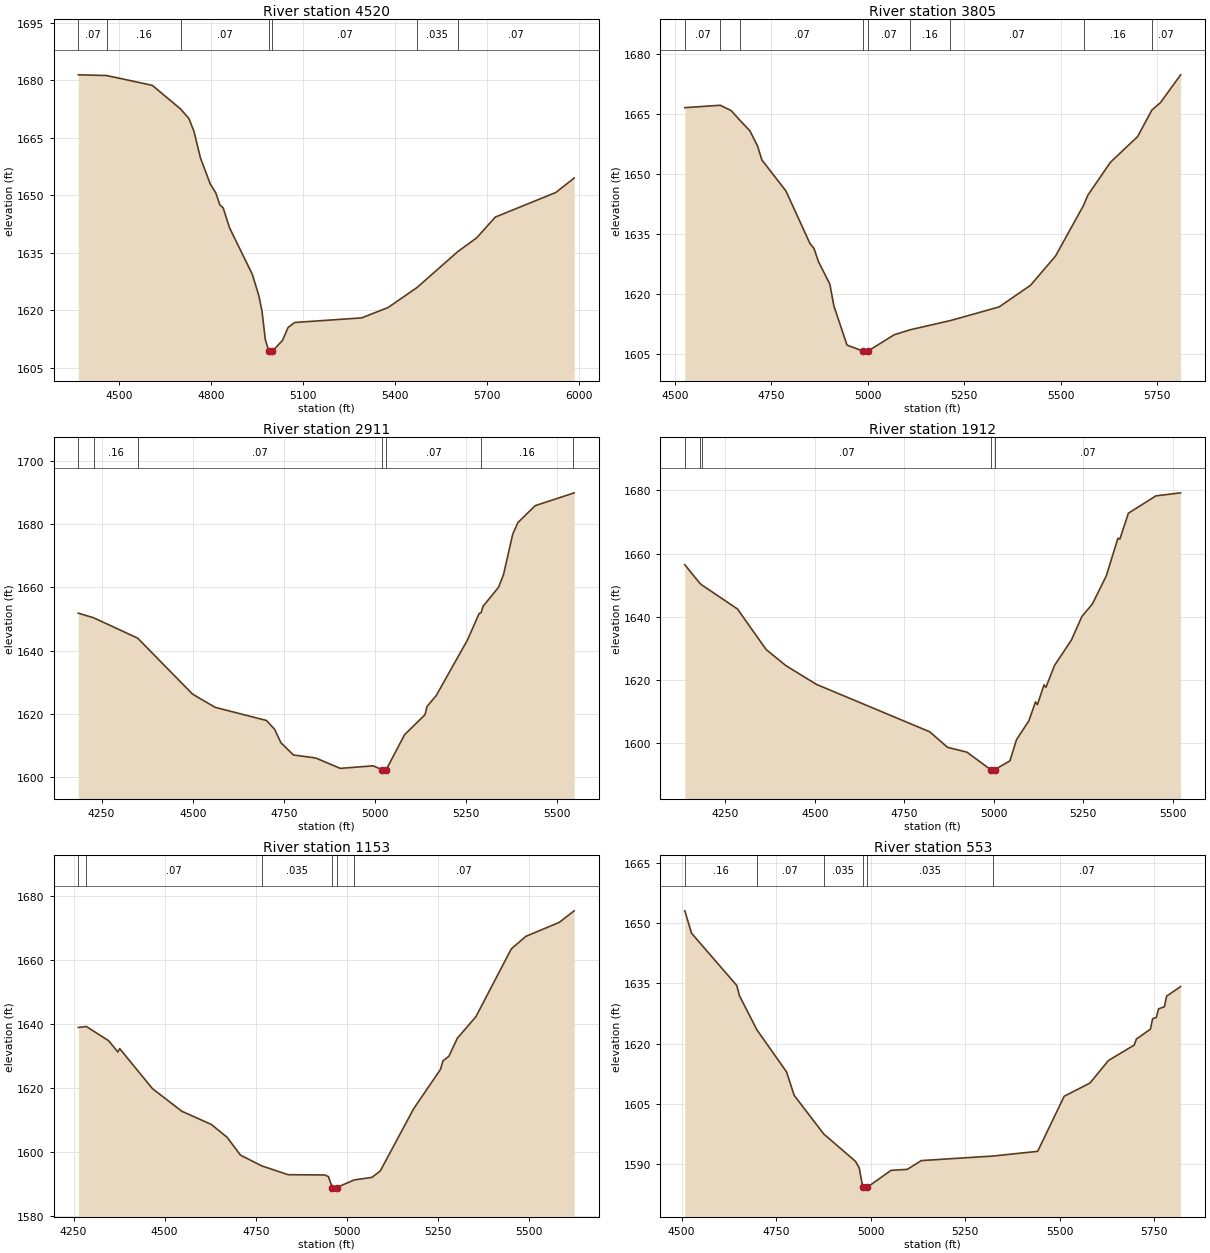
Type RM Length L Ch R = 1,4520,715,715,715
BEGIN DESCRIPTION:
Mapping XS e7ac0ba2
END DESCRIPTION:
XS GIS Cut Line= 3
      1652708.66      6972280.83      1653302.43      6972075.09
      1654231.08      6971734.33
#Sta/Elev= 30
  4368.0 1681.42  4460.0 1681.24  4609.3 1678.68  4701.5 1672.52  4728.6 1670.05
  4745.1 1666.73  4766.3 1659.80  4798.0 1653.04  4816.7 1650.60  4829.8 1647.49
  4840.4 1646.76  4861.5 1641.51  4935.6 1629.41  4956.8 1623.86  4967.2 1619.81
  4978.0 1612.43  4989.3 1609.36  4989.8 1608.86  5001.0 1609.36  5034.0 1612.17
  5052.4 1615.56  5073.7 1616.85  5292.4 1618.05  5378.6 1620.75  5472.9 1625.96
  5605.1 1635.27  5667.5 1638.91  5728.5 1644.34  5925.9 1650.75  5985.6 1654.50
#Mann=7,-1,0
  4368.0    0.07       0  4460.0    0.16       0  4701.5    0.07       0
  4989.3    0.07       0  5001.0    0.07       0  5472.9   0.035       0
  5605.1    0.07       0
Bank Sta=4989.3,5001
Exp/Cntr=0.3,0.1

Type RM Length L Ch R = 1,3805,894,894,894
BEGIN DESCRIPTION:
Mapping XS 4a156439
END DESCRIPTION:
XS GIS Cut Line= 3
      1653252.29      6972764.33      1653708.03      6972638.46
      1654484.98      6972399.74
#Sta/Elev= 30
  4525.4 1666.56  4617.2 1667.16  4645.3 1665.85  4669.4 1663.30  4694.2 1660.76
  4714.0 1656.99  4725.3 1653.48  4787.6 1645.73  4849.8 1632.62  4860.2 1631.39
  4872.1 1628.03  4901.3 1622.48  4912.1 1616.95  4946.0 1607.18  4988.1 1605.67
  4988.6 1605.17  5000.0 1605.67  5068.3 1609.76  5109.7 1611.01  5214.2 1613.32
  5340.3 1616.72  5422.0 1622.15  5486.7 1629.46  5559.3 1642.12  5570.4 1644.65
  5628.8 1652.88  5699.5 1659.33  5736.5 1665.97  5758.7 1667.81  5811.0 1674.77
#Mann=9,-1,0
  4525.4    0.07       0  4617.2    0.16       0  4669.4    0.07       0
  4988.1   0.035       0  5000.0    0.07       0  5109.7    0.16       0
  5214.2    0.07       0  5559.3    0.16       0  5736.5    0.07       0
Bank Sta=4988.1,5000
Exp/Cntr=0.3,0.1

Type RM Length L Ch R = 1,2911,999,999,999
BEGIN DESCRIPTION:
Mapping XS 1ca1f801
END DESCRIPTION:
XS GIS Cut Line= 3
      1653474.92      6972986.77      1654206.26      6973344.84
      1654720.31      6973529.20
#Sta/Elev= 30
  4186.2 1651.85  4228.1 1650.40  4348.8 1643.99  4499.8 1626.29  4561.8 1622.13
  4702.4 1617.99  4724.9 1615.18  4741.8 1611.00  4776.4 1607.11  4837.4 1606.16
  4904.9 1602.88  4994.9 1603.68  5019.2 1602.51  5019.7 1602.01  5031.2 1602.51
  5081.4 1613.52  5137.3 1619.80  5142.9 1622.41  5168.3 1625.88  5254.1 1643.44
  5286.0 1651.78  5291.1 1651.96  5296.6 1654.02  5339.1 1660.01  5352.8 1664.04
  5378.2 1676.82  5392.2 1680.43  5439.7 1685.77  5544.3 1689.72  5546.6 1689.82
#Mann=7,-1,0
  4186.2    0.07       0  4228.1    0.16       0  4348.8    0.07       0
  5019.2    0.07       0  5031.2    0.07       0  5291.1    0.16       0
  5544.3    0.07       0
Bank Sta=5019.2,5031.2
Exp/Cntr=0.3,0.1

Type RM Length L Ch R = 1,1912,759,759,759
BEGIN DESCRIPTION:
Mapping XS b845a701
END DESCRIPTION:
XS GIS Cut Line= 3
      1653079.94      6972880.40      1653383.78      6973687.72
      1653585.58      6974169.46
#Sta/Elev= 30
  4136.9 1656.46  4178.8 1650.58  4185.9 1649.93  4284.1 1642.42  4364.1 1629.57
  4419.2 1624.48  4504.6 1618.53  4821.0 1603.50  4870.7 1598.58  4925.0 1597.04
  4990.9 1591.53  4991.4 1591.03  5003.0 1591.53  5045.0 1594.28  5063.4 1601.00
  5098.0 1607.00  5116.4 1612.96  5121.8 1612.09  5140.2 1618.37  5145.6 1617.58
  5169.4 1624.49  5216.6 1632.56  5246.1 1640.06  5275.4 1644.02  5314.2 1652.94
  5346.7 1664.86  5352.1 1664.58  5375.9 1672.78  5452.7 1678.27  5521.8 1679.24
#Mann=5,-1,0
  4136.9    0.07       0  4178.8    0.16       0  4185.9    0.07       0
  4990.9    0.07       0  5003.0    0.07       0
Bank Sta=4990.9,5003
Exp/Cntr=0.3,0.1

Type RM Length L Ch R = 1,1153,600,600,600
BEGIN DESCRIPTION:
Mapping XS 4762fea3
END DESCRIPTION:
XS GIS Cut Line= 3
      1652599.06      6972905.22      1652673.71      6973643.02
      1652935.29      6974204.29
#Sta/Elev= 30
  4263.1 1638.94  4285.1 1639.25  4346.3 1634.79  4371.6 1631.28  4376.6 1632.34
  4466.5 1619.83  4547.3 1612.76  4627.7 1608.67  4671.4 1604.64  4708.1 1599.06
  4767.1 1595.67  4838.8 1592.95  4939.3 1592.86  4949.4 1592.38  4960.0 1588.94
  4960.5 1588.44  4972.2 1588.94  5019.9 1591.31  5068.9 1592.12  5091.7 1594.10
  5183.2 1613.52  5257.3 1625.90  5263.9 1628.52  5280.2 1629.95  5303.1 1635.55
  5354.3 1642.31  5451.5 1663.50  5491.6 1667.41  5583.0 1671.76  5623.9 1675.37
#Mann=6,-1,0
  4263.1    0.16       0  4285.1    0.07       0  4767.1   0.035       0
  4960.0   0.035       0  4972.2   0.035       0  5019.9    0.07       0
Bank Sta=4960,4972.2
Exp/Cntr=0.3,0.1

Type RM Length L Ch R = 1,553,503,503,503
BEGIN DESCRIPTION:
Mapping XS fc17a281
END DESCRIPTION:
XS GIS Cut Line= 3
      1652067.80      6972952.02      1652142.46      6973439.89
      1652559.92      6974143.17
#Sta/Elev= 30
  4508.7 1653.02  4526.6 1647.45  4646.3 1634.46  4653.4 1631.91  4699.3 1623.48
  4777.8 1613.01  4798.0 1607.18  4876.2 1597.58  4959.9 1590.81  4970.0 1589.17
  4979.4 1584.38  4979.9 1583.88  4991.7 1584.38  5054.3 1588.55  5097.1 1588.79
  5134.2 1590.97  5323.9 1592.10  5442.0 1593.27  5512.2 1606.96  5580.4 1610.24
  5629.1 1615.83  5697.3 1619.67  5703.2 1621.17  5740.2 1623.62  5746.0 1626.21
  5755.8 1626.53  5761.6 1628.66  5777.2 1629.18  5783.0 1631.82  5820.1 1634.21
#Mann=6,-1,0
  4508.7    0.16       0  4699.3    0.07       0  4876.2   0.035       0
  4979.4   0.035       0  4991.7   0.035       0  5323.9    0.07       0
Bank Sta=4979.4,4991.7
Exp/Cntr=0.3,0.1

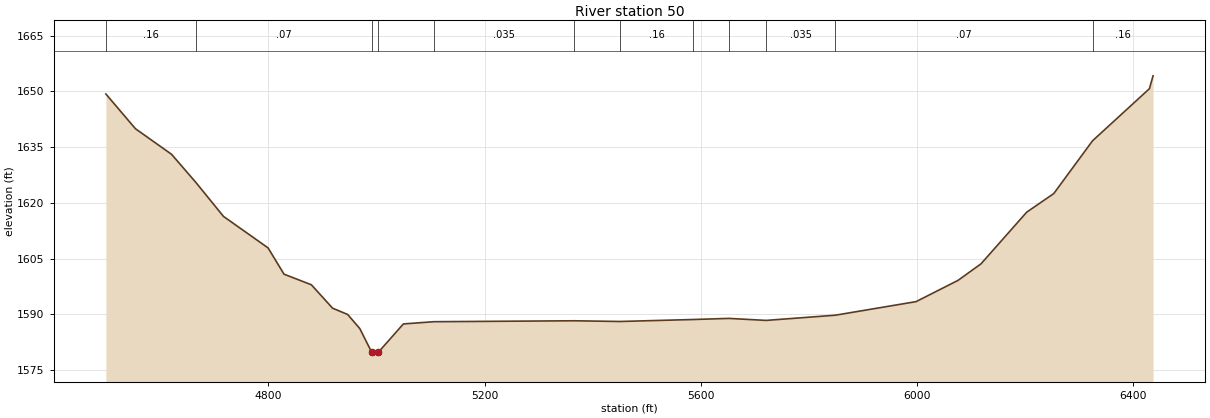
Type RM Length L Ch R = 1,50,0,0,0
BEGIN DESCRIPTION:
Chimney Creek 1144 1.0
END DESCRIPTION:
XS GIS Cut Line= 3
      1651876.66      6973038.91      1651655.05      6973488.11
      1652620.11      6974552.83
#Sta/Elev= 30
  4499.1 1649.29  4553.8 1639.95  4620.7 1633.06  4665.8 1625.47  4716.6 1616.38
  4799.2 1607.90  4828.8 1600.82  4879.3 1597.98  4918.6 1591.68  4946.6 1589.98
  4969.1 1586.17  4991.0 1579.82  4991.5 1579.32  5003.3 1579.82  5049.6 1587.44
  5106.0 1588.04  5366.0 1588.29  5450.3 1588.10  5585.7 1588.63  5652.1 1588.93
  5721.0 1588.39  5849.0 1589.79  5998.4 1593.44  6076.1 1599.16  6118.7 1603.62
  6203.2 1617.51  6253.2 1622.50  6325.1 1636.72  6430.3 1650.72  6437.0 1654.18
#Mann=12,-1,0
  4499.1    0.16       0  4665.8    0.07       0  4991.0    0.07       0
  5003.3    0.07       0  5106.0   0.035       0  5366.0    0.07       0
  5450.3    0.16       0  5585.7   0.035       0  5652.1    0.07       0
  5721.0   0.035       0  5849.0    0.07       0  6325.1    0.16       0
Bank Sta=4991,5003.3
Exp/Cntr=0.3,0.1

Chan Stop Cuts=-1