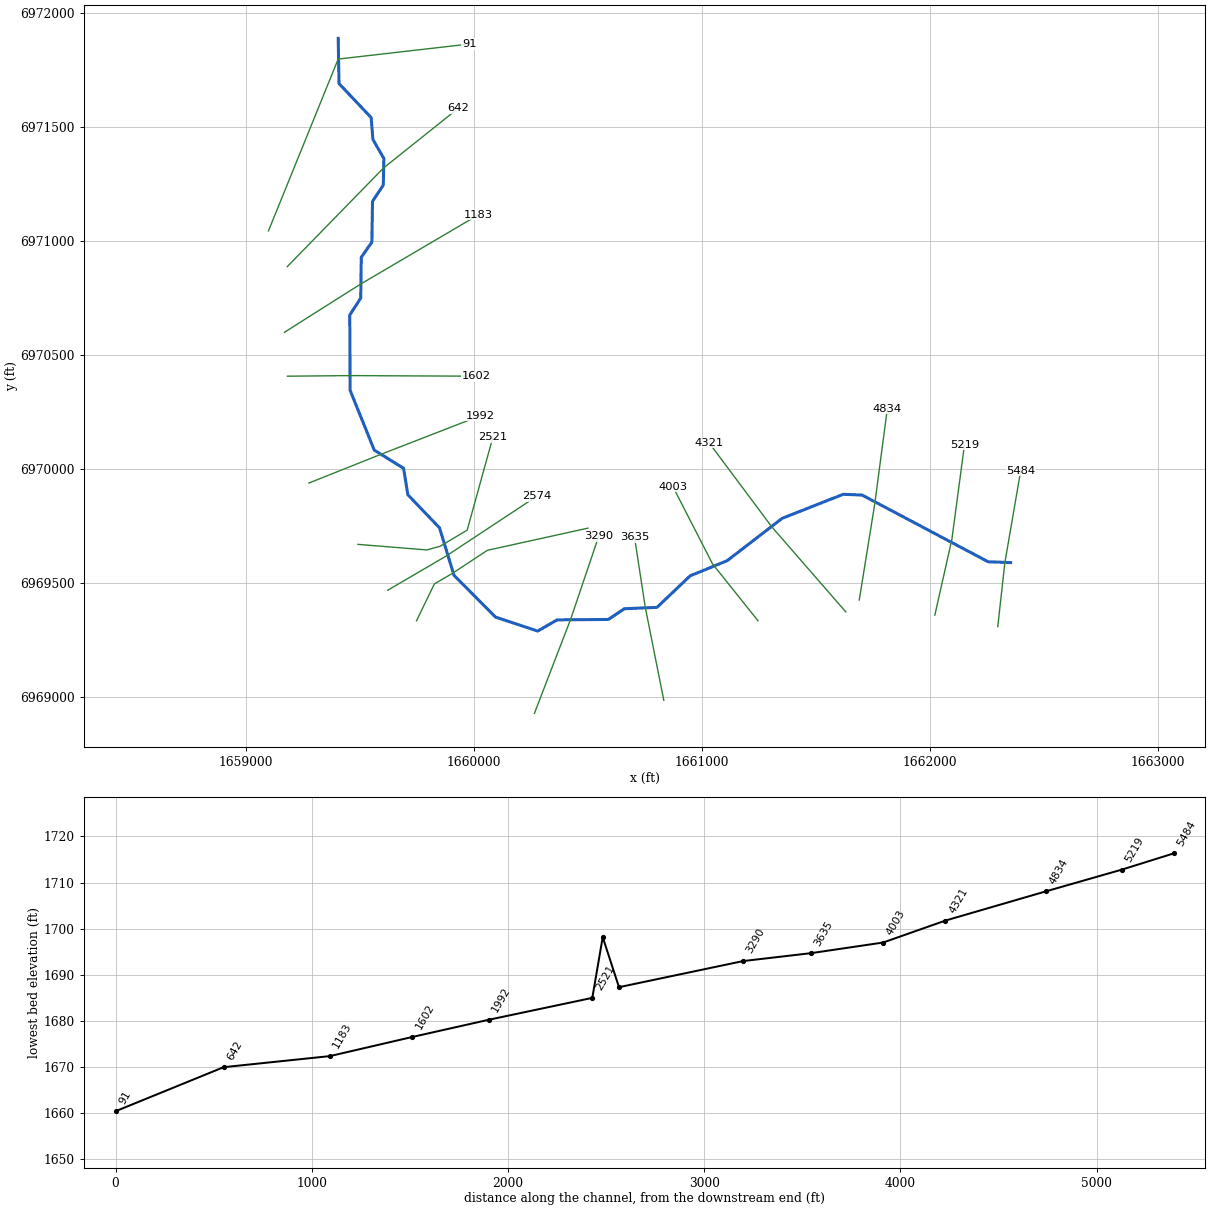
--- Chimney Creek 1145.prj (project) ---

Proj Title=Chimney Creek 1145 Base Level Engineering
Current Plan=p01
Default Exp/Contr=0.3,0.1
English Units
Geom File=g01
Flow File=f01
Plan File=p01
BEGIN DESCRIPTION:
Chimney Creek 1145
END DESCRIPTION:

--- Chimney Creek 1145.p01 (plan) ---

Plan Title=Multiple Run
Short Identifier=Multiple
Geom File=g01
Flow File=f01
Subcritical Flow
K Sum by GR= 0
Std Step Tol= 0.01
Critical Tol= 0.01
Num of Std Step Trials= 20
Max Error Tol= 0.3
Flow Tol Ratio= 0.001
Split Flow NTrial= 30
Split Flow Tol= 0.02
Split Flow Ratio= 0.02
Log Output Level= 0
Friction Slope Method= 1
Unsteady Friction Slope Method= 2
Unsteady Bridges Friction Slope Method= 1
Parabolic Critical Depth
Global Vel Dist=  1 , 1 , 1
Global Log Level= 0
CheckData=True
Encroach Param= -1, 0, 0, 0
BEGIN DESCRIPTION:
Multiple Run
END DESCRIPTION:

--- Chimney Creek 1145.f01 (steady flow) ---

Flow Title=Multiple
Number of Profiles=7
Profile Names=10-year,25-year,50-year,1pct_min,100-year,1pct_plu,500-year
River Rch & RM= Chimney Creek 11,Reach-1,5484
     256     355     438     269     537    1072     818
River Rch & RM= Chimney Creek 11,Reach-1,3635
     322     453     563     349     696    1388    1076
Boundary for River Rch & Prof#=Chimney Creek 11,Reach-1,1
Up Type=0
Dn Type=3
Dn Slope=0.005
Boundary for River Rch & Prof#=Chimney Creek 11,Reach-1,2
Up Type=0
Dn Type=3
Dn Slope=0.005
Boundary for River Rch & Prof#=Chimney Creek 11,Reach-1,3
Up Type=0
Dn Type=3
Dn Slope=0.005
Boundary for River Rch & Prof#=Chimney Creek 11,Reach-1,4
Up Type=0
Dn Type=3
Dn Slope=0.005
Boundary for River Rch & Prof#=Chimney Creek 11,Reach-1,5
Up Type=0
Dn Type=3
Dn Slope=0.005
Boundary for River Rch & Prof#=Chimney Creek 11,Reach-1,6
Up Type=0
Dn Type=3
Dn Slope=0.005
Boundary for River Rch & Prof#=Chimney Creek 11,Reach-1,7
Up Type=0
Dn Type=3
Dn Slope=0.005

--- Chimney Creek 1145.g01 (geometry) ---

Geom Title=Existing Conditions

River Reach=Chimney Creek 11,Reach-1
Reach XY= 30
      1662355.00      6969588.00      1662256.50      6969591.63
      1661703.42      6969884.33      1661620.27      6969887.62
      1661352.71      6969782.16      1661111.05      6969596.16
      1660948.94      6969529.86      1660803.53      6969391.54
      1660660.53      6969385.61      1660589.78      6969338.52
      1660365.50      6969336.78      1660280.00      6969287.60
      1660095.32      6969348.76      1659913.14      6969531.94
      1659849.48      6969740.43      1659710.53      6969885.58
      1659691.74      6970001.65      1659563.02      6970081.66
      1659457.26      6970343.94      1659455.68      6970674.08
      1659503.78      6970748.51      1659506.22      6970927.49
      1659552.74      6970993.94      1659555.52      6971172.78
      1659602.75      6971243.94      1659605.31      6971360.83
      1659557.36      6971443.98      1659549.48      6971540.43
      1659408.53      6971689.46      1659405.00      6971888.00

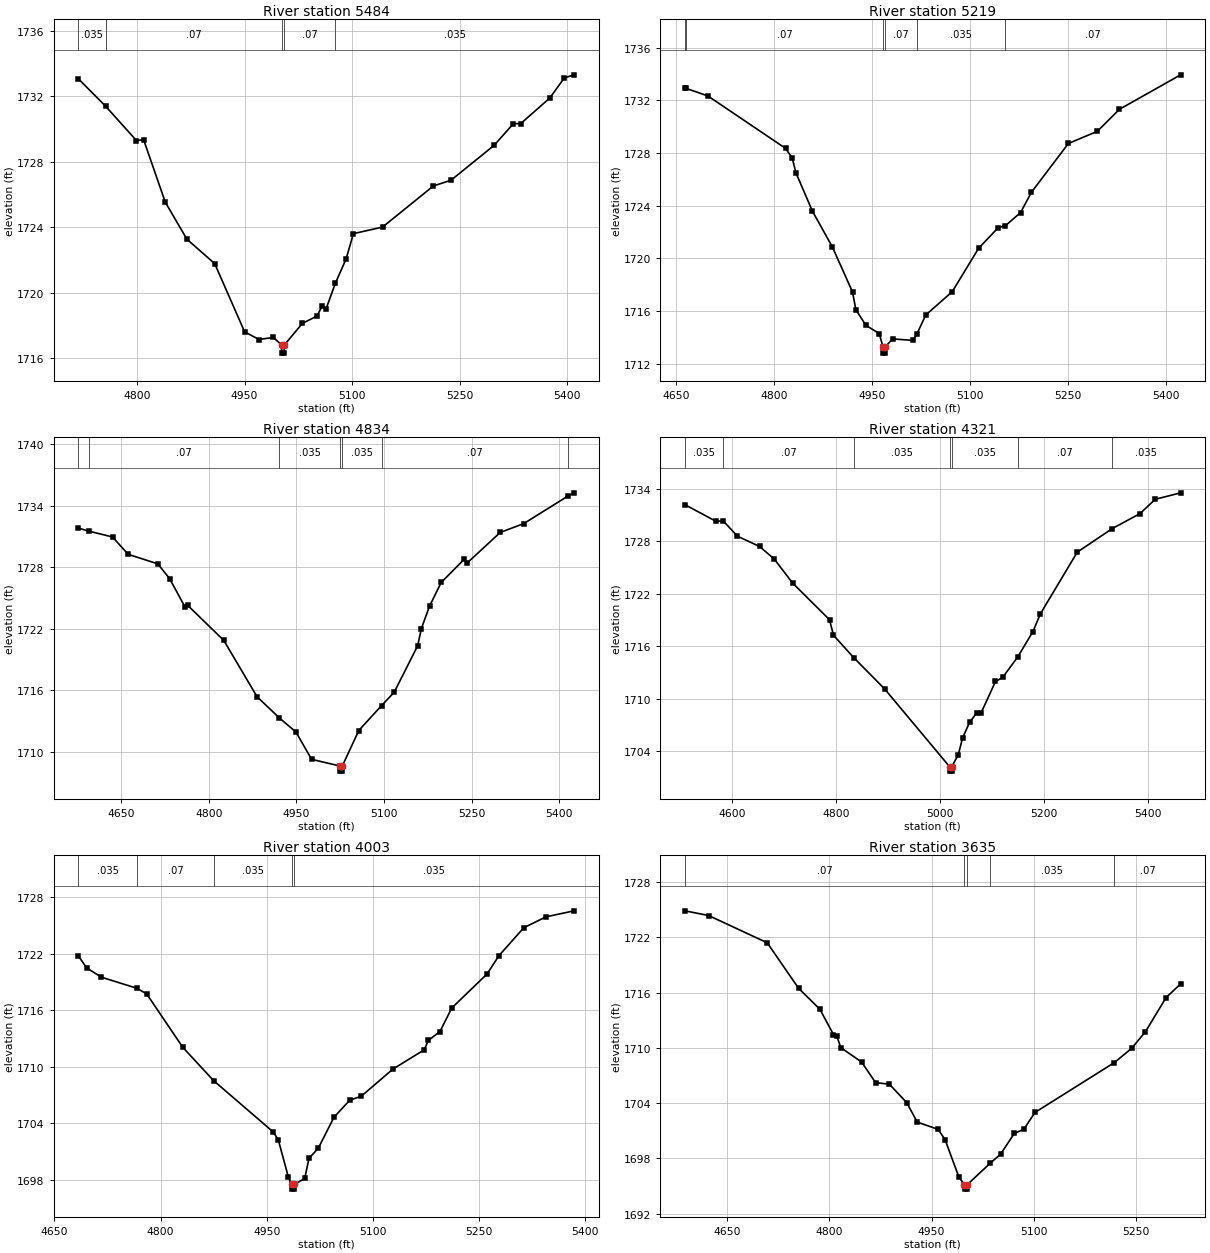
Type RM Length L Ch R = 1,5484,265,265,265
BEGIN DESCRIPTION:
Chimney Creek 1145 11.0
END DESCRIPTION:
XS GIS Cut Line= 3
      1662298.57      6969307.44      1662329.73      6969587.71
      1662399.26      6969991.47
#Sta/Elev= 30
  4718.0 1733.06  4756.4 1731.37  4799.1 1729.29  4809.1 1729.34  4839.3 1725.53
  4869.5 1723.27  4908.3 1721.78  4950.0 1717.62  4970.1 1717.15  4990.2 1717.28
  5001.5 1716.82  5001.7 1716.32  5005.2 1716.32  5005.5 1716.82  5030.7 1718.14
  5051.0 1718.58  5058.3 1719.21  5063.4 1718.99  5076.7 1720.59  5091.6 1722.07
  5101.8 1723.61  5142.4 1724.01  5213.4 1726.52  5238.0 1726.87  5297.9 1728.99
  5325.0 1730.32  5335.1 1730.32  5375.7 1731.88  5396.0 1733.11  5409.7 1733.30
#Mann=5,-1,0
  4718.0   0.035       0  4756.4    0.07       0  5001.5    0.07       0
  5005.5    0.07       0  5076.7   0.035       0
Bank Sta=5001.5,5005.5
Exp/Cntr=0.3,0.1

Type RM Length L Ch R = 1,5219,385,385,385
BEGIN DESCRIPTION:
Mapping XS b7bb92c0
END DESCRIPTION:
XS GIS Cut Line= 3
      1662022.51      6969357.69      1662097.17      6969689.34
      1662152.53      6970104.52
#Sta/Elev= 30
  4663.6 1732.92  4665.3 1732.92  4698.7 1732.35  4817.7 1728.36  4827.9 1727.62
  4833.7 1726.49  4858.7 1723.60  4889.4 1720.86  4920.2 1717.44  4925.3 1716.10
  4940.7 1714.90  4961.2 1714.28  4966.6 1713.29  4966.8 1712.79  4970.3 1712.79
  4970.6 1713.29  4981.7 1713.87  5012.3 1713.76  5018.4 1714.21  5032.5 1715.70
  5072.8 1717.46  5113.2 1720.76  5143.4 1722.34  5154.3 1722.48  5177.5 1723.48
  5193.9 1725.01  5250.6 1728.73  5294.8 1729.65  5328.8 1731.33  5422.4 1733.95
#Mann=6,-1,0
  4663.6   0.035       0  4665.3    0.07       0  4966.6    0.07       0
  4970.6    0.07       0  5018.4   0.035       0  5154.3    0.07       0
Bank Sta=4966.6,4970.6
Exp/Cntr=0.3,0.1

Type RM Length L Ch R = 1,4834,513,513,513
BEGIN DESCRIPTION:
Mapping XS e09a70db
END DESCRIPTION:
XS GIS Cut Line= 3
      1661690.91      6969423.66      1661758.63      6969843.85
      1661814.12      6970263.49
#Sta/Elev= 30
  4576.6 1731.81  4594.9 1731.51  4635.2 1730.94  4662.0 1729.25  4712.7 1728.32
  4732.9 1726.88  4758.8 1724.16  4763.9 1724.27  4825.7 1720.85  4882.5 1715.37
  4920.6 1713.30  4949.3 1711.91  4976.0 1709.25  5024.6 1708.60  5024.8 1708.10
  5028.3 1708.10  5028.6 1708.60  5056.8 1712.06  5095.9 1714.50  5117.4 1715.79
  5157.7 1720.34  5164.0 1722.01  5177.9 1724.19  5198.0 1726.51  5237.4 1728.77
  5242.5 1728.41  5298.9 1731.38  5339.3 1732.25  5414.6 1734.92  5425.5 1735.25
#Mann=7,-1,0
  4576.6   0.035       0  4594.9    0.07       0  4920.6   0.035       0
  5024.6   0.035       0  5028.6   0.035       0  5095.9    0.07       0
  5414.6   0.035       0
Bank Sta=5024.6,5028.6
Exp/Cntr=0.3,0.1

Type RM Length L Ch R = 1,4321,318,318,318
BEGIN DESCRIPTION:
Mapping XS f84c2202
END DESCRIPTION:
XS GIS Cut Line= 3
      1661631.92      6969371.60      1661307.24      6969744.89
      1661031.86      6970113.81
#Sta/Elev= 30
  4508.5 1732.16  4567.9 1730.28  4582.7 1730.29  4609.8 1728.56  4652.4 1727.39
  4680.8 1725.95  4716.0 1723.22  4787.2 1719.03  4794.8 1717.26  4833.7 1714.71
  4893.5 1711.12  5018.6 1702.25  5018.8 1701.75  5022.3 1701.75  5022.6 1702.25
  5035.2 1703.60  5043.5 1705.54  5057.0 1707.30  5070.6 1708.39  5079.0 1708.37
  5106.9 1711.98  5120.7 1712.44  5149.7 1714.77  5179.0 1717.67  5193.6 1719.72
  5264.5 1726.74  5331.6 1729.42  5385.4 1731.14  5414.6 1732.77  5463.6 1733.51
#Mann=7,-1,0
  4508.5   0.035       0  4582.7    0.07       0  4833.7   0.035       0
  5018.6   0.035       0  5022.6   0.035       0  5149.7    0.07       0
  5331.6   0.035       0
Bank Sta=5018.6,5022.6
Exp/Cntr=0.3,0.1

Type RM Length L Ch R = 1,4003,368,368,368
BEGIN DESCRIPTION:
Mapping XS efde9730
END DESCRIPTION:
XS GIS Cut Line= 3
      1661246.64      6969332.75      1661047.00      6969582.74
      1660873.38      6969921.30
#Sta/Elev= 30
  4683.9 1721.79  4695.8 1720.50  4716.6 1719.52  4767.2 1718.33  4780.6 1717.73
  4831.4 1712.07  4875.0 1708.52  4959.4 1703.05  4966.4 1702.21  4980.8 1698.22
  4985.2 1697.48  4985.4 1696.98  4988.9 1696.98  4989.2 1697.48  5003.8 1698.12
  5009.7 1700.25  5022.9 1701.33  5045.1 1704.63  5067.3 1706.43  5083.8 1706.87
  5128.2 1709.74  5172.6 1711.80  5178.3 1712.79  5194.8 1713.74  5211.4 1716.24
  5261.4 1719.87  5278.0 1721.80  5313.2 1724.78  5344.6 1725.94  5384.3 1726.58
#Mann=5,-1,0
  4683.9   0.035       0  4767.2    0.07       0  4875.0   0.035       0
  4985.2   0.035       0  4989.2   0.035       0
Bank Sta=4985.2,4989.2
Exp/Cntr=0.3,0.1

Type RM Length L Ch R = 1,3635,345,345,345
BEGIN DESCRIPTION:
Mapping XS e2d43c4a
END DESCRIPTION:
XS GIS Cut Line= 3
      1660833.45      6968983.81      1660751.86      6969393.50
      1660704.98      6969699.09
#Sta/Elev= 30
  4588.2 1724.87  4623.1 1724.36  4709.0 1721.40  4755.0 1716.46  4786.2 1714.19
  4806.1 1711.44  4811.2 1711.24  4816.8 1710.03  4847.4 1708.46  4867.8 1706.23
  4888.2 1706.05  4913.4 1704.06  4929.0 1701.94  4959.4 1701.16  4969.7 1700.05
  4990.1 1695.95  4998.2 1695.17  4998.4 1694.67  5002.2 1694.67  5002.5 1695.17
  5036.3 1697.51  5051.0 1698.45  5071.2 1700.71  5085.3 1701.17  5101.5 1702.99
  5217.7 1708.39  5243.2 1709.94  5263.4 1711.74  5293.8 1715.46  5315.1 1716.94
#Mann=5,-1,0
  4588.2    0.07       0  4998.2    0.07       0  5002.5    0.07       0
  5036.3   0.035       0  5217.7    0.07       0
Bank Sta=4998.2,5002.5
Exp/Cntr=0.3,0.1

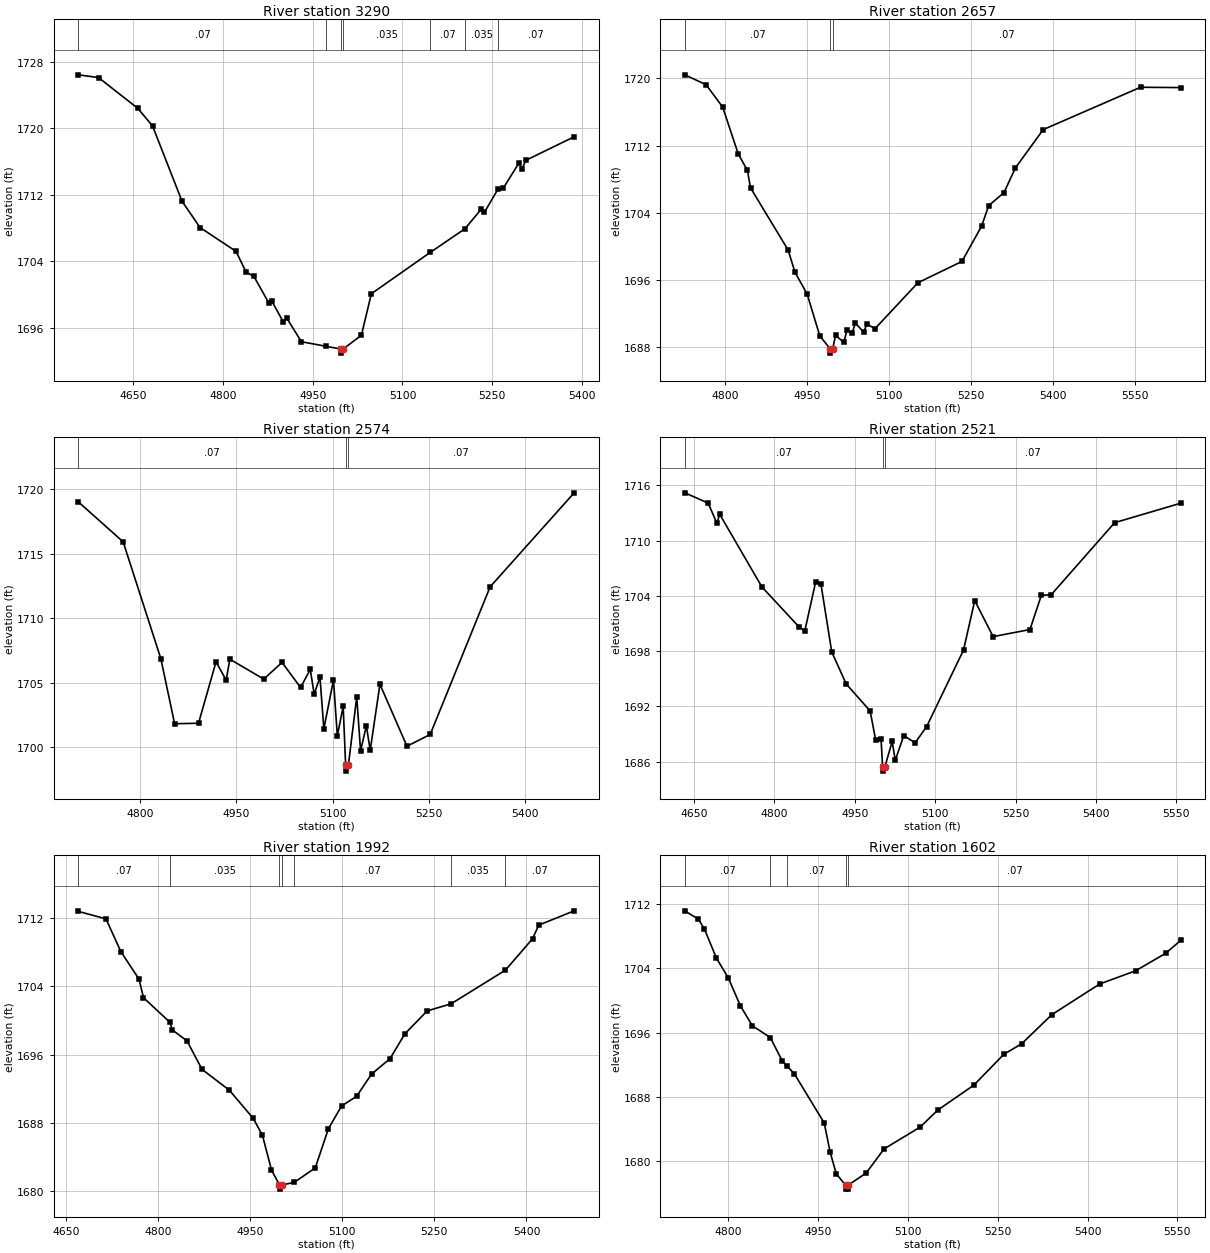
Type RM Length L Ch R = 1,3290,633,633,633
BEGIN DESCRIPTION:
Mapping XS ca24eec5
END DESCRIPTION:
XS GIS Cut Line= 3
      1660265.76      6968926.52      1660425.47      6969341.42
      1660548.21      6969704.45
#Sta/Elev= 30
  4558.8 1726.42  4592.5 1726.09  4658.1 1722.39  4682.8 1720.26  4731.8 1711.24
  4762.0 1708.06  4822.0 1705.20  4839.0 1702.69  4852.0 1702.18  4876.6 1699.01
  4882.0 1699.18  4901.3 1696.68  4906.6 1697.18  4931.3 1694.33  4973.1 1693.77
  4996.7 1693.46  4997.0 1692.96  5001.1 1693.46  5031.4 1695.11  5048.0 1700.10
  5146.1 1705.06  5204.3 1707.91  5231.4 1710.26  5236.7 1709.88  5259.6 1712.70
  5268.1 1712.77  5294.3 1715.81  5299.6 1715.10  5305.9 1716.14  5386.6 1718.97
#Mann=7,-1,0
  4558.8    0.07       0  4973.1   0.035       0  4996.7   0.035       0
  5001.1   0.035       0  5146.1    0.07       0  5204.3   0.035       0
  5259.6    0.07       0
Bank Sta=4996.7,5001.1
Exp/Cntr=0.3,0.1

Type RM Length L Ch R = 1,2657,83,83,83
BEGIN DESCRIPTION:
Mapping XS 5db59ec0
END DESCRIPTION:
XS GIS Cut Line= 5
      1659748.66      6969332.89      1659826.77      6969494.31
      1659906.63      6969541.19      1660059.41      6969641.88
      1660500.22      6969739.07
#Sta/Elev= 30
  4726.3 1720.43  4765.3 1719.25  4795.7 1716.57  4823.8 1711.04  4840.8 1709.04
  4846.4 1706.98  4915.2 1699.56  4927.7 1696.92  4950.0 1694.31  4973.1 1689.34
  4992.2 1687.79  4992.5 1687.29  4996.6 1687.79  5001.9 1689.41  5017.0 1688.57
  5023.0 1690.10  5032.0 1689.63  5038.0 1690.89  5053.1 1689.79  5059.1 1690.72
  5074.2 1690.22  5152.4 1695.67  5232.9 1698.21  5268.9 1702.42  5281.7 1704.85
  5309.8 1706.41  5330.6 1709.35  5381.5 1713.91  5559.3 1718.95  5632.6 1718.91
#Mann=3,-1,0
  4726.3    0.07       0  4992.2    0.07       0  4996.6    0.07       0
Bank Sta=4992.2,4996.6
Exp/Cntr=0.3,0.1

Type RM Length L Ch R = 1,2574,53,53,53
BEGIN DESCRIPTION:
Mapping XS b20c9df2
END DESCRIPTION:
XS GIS Cut Line= 3
      1659621.90      6969466.53      1659877.12      6969615.84
      1660274.68      6969877.99
#Sta/Elev= 30
  4704.3 1719.01  4774.1 1715.91  4832.7 1706.87  4854.2 1701.82  4891.4 1701.86
  4918.7 1706.62  4934.4 1705.20  4940.2 1706.82  4993.0 1705.28  5021.4 1706.57
  5050.3 1704.63  5065.4 1706.03  5071.4 1704.12  5080.5 1705.42  5086.5 1701.43
  5101.5 1705.20  5107.5 1700.89  5116.6 1703.16  5120.4 1698.65  5120.7 1698.15
  5124.8 1698.65  5137.7 1703.89  5143.7 1699.73  5152.7 1701.66  5158.7 1699.76
  5173.8 1704.88  5215.9 1700.08  5252.1 1700.99  5345.4 1712.43  5476.2 1719.71
#Mann=3,-1,0
  4704.3    0.07       0  5120.4    0.07       0  5124.8    0.07       0
Bank Sta=5120.4,5124.8
Exp/Cntr=0.3,0.1

Type RM Length L Ch R = 1,2521,529,529,529
BEGIN DESCRIPTION:
Mapping XS 07eace8b
END DESCRIPTION:
XS GIS Cut Line= 5
      1659491.69      6969667.93      1659793.79      6969643.62
      1659851.08      6969659.24      1659970.87      6969730.42
      1660083.71      6970138.40
#Sta/Elev= 30
  4632.9 1715.18  4676.4 1714.07  4692.9 1711.87  4697.9 1712.86  4776.7 1704.97
  4846.9 1700.57  4856.9 1700.22  4877.0 1705.50  4887.0 1705.24  4907.1 1697.90
  4934.1 1694.43  4978.7 1691.50  4989.1 1688.32  4999.0 1688.49  5002.0 1685.47
  5002.3 1684.97  5006.4 1685.47  5019.8 1688.19  5025.6 1686.14  5041.3 1688.82
  5062.7 1688.05  5084.1 1689.80  5152.9 1698.11  5173.9 1703.48  5208.2 1699.57
  5276.9 1700.34  5298.2 1704.07  5316.4 1704.11  5434.9 1711.94  5558.0 1714.05
#Mann=3,-1,0
  4632.9    0.07       0  5002.0    0.07       0  5006.4    0.07       0
Bank Sta=5002,5006.4
Exp/Cntr=0.3,0.1

Type RM Length L Ch R = 1,1992,390,390,390
BEGIN DESCRIPTION:
Mapping XS 03a4fe92
END DESCRIPTION:
XS GIS Cut Line= 3
      1659276.43      6969937.02      1659585.45      6970060.29
      1660028.16      6970232.16
#Sta/Elev= 30
  4670.1 1712.80  4715.1 1711.93  4739.4 1708.08  4769.0 1704.84  4776.2 1702.68
  4819.5 1699.77  4822.9 1698.91  4847.2 1697.60  4871.5 1694.27  4916.2 1691.81
  4955.0 1688.51  4970.0 1686.52  4984.7 1682.46  4997.6 1680.71  4997.9 1680.21
  5002.1 1680.71  5021.7 1681.00  5056.0 1682.70  5077.4 1687.30  5098.9 1689.97
  5123.3 1691.10  5147.8 1693.72  5177.7 1695.51  5202.2 1698.46  5238.3 1701.12
  5277.3 1701.96  5365.8 1705.91  5409.9 1709.59  5420.0 1711.19  5477.7 1712.87
#Mann=7,-1,0
  4670.1    0.07       0  4819.5   0.035       0  4997.6   0.035       0
  5002.1   0.035       0  5021.7    0.07       0  5277.3   0.035       0
  5365.8    0.07       0
Bank Sta=4997.6,5002.1
Exp/Cntr=0.3,0.1

Type RM Length L Ch R = 1,1602,419,419,419
BEGIN DESCRIPTION:
Mapping XS 0eae571e
END DESCRIPTION:
XS GIS Cut Line= 3
      1659182.24      6970405.77      1659455.68      6970408.38
      1660010.22      6970405.77
#Sta/Elev= 30
  4727.5 1711.19  4750.3 1710.14  4760.3 1708.92  4780.3 1705.29  4800.3 1702.80
  4820.3 1699.34  4840.3 1696.85  4870.3 1695.38  4890.3 1692.46  4898.6 1691.80
  4910.3 1690.87  4960.3 1684.73  4970.3 1681.07  4980.3 1678.40  4995.9 1676.97
  4996.2 1676.47  5000.1 1676.47  5000.4 1676.97  5030.3 1678.47  5060.3 1681.49
  5120.3 1684.20  5150.3 1686.35  5210.3 1689.45  5260.3 1693.29  5290.3 1694.62
  5340.3 1698.23  5420.3 1702.06  5480.3 1703.71  5530.3 1705.88  5555.5 1707.49
#Mann=5,-1,0
  4727.5    0.07       0  4870.3   0.035       0  4898.6    0.07       0
  4995.9    0.07       0  5000.4    0.07       0
Bank Sta=4995.9,5000.4
Exp/Cntr=0.3,0.1

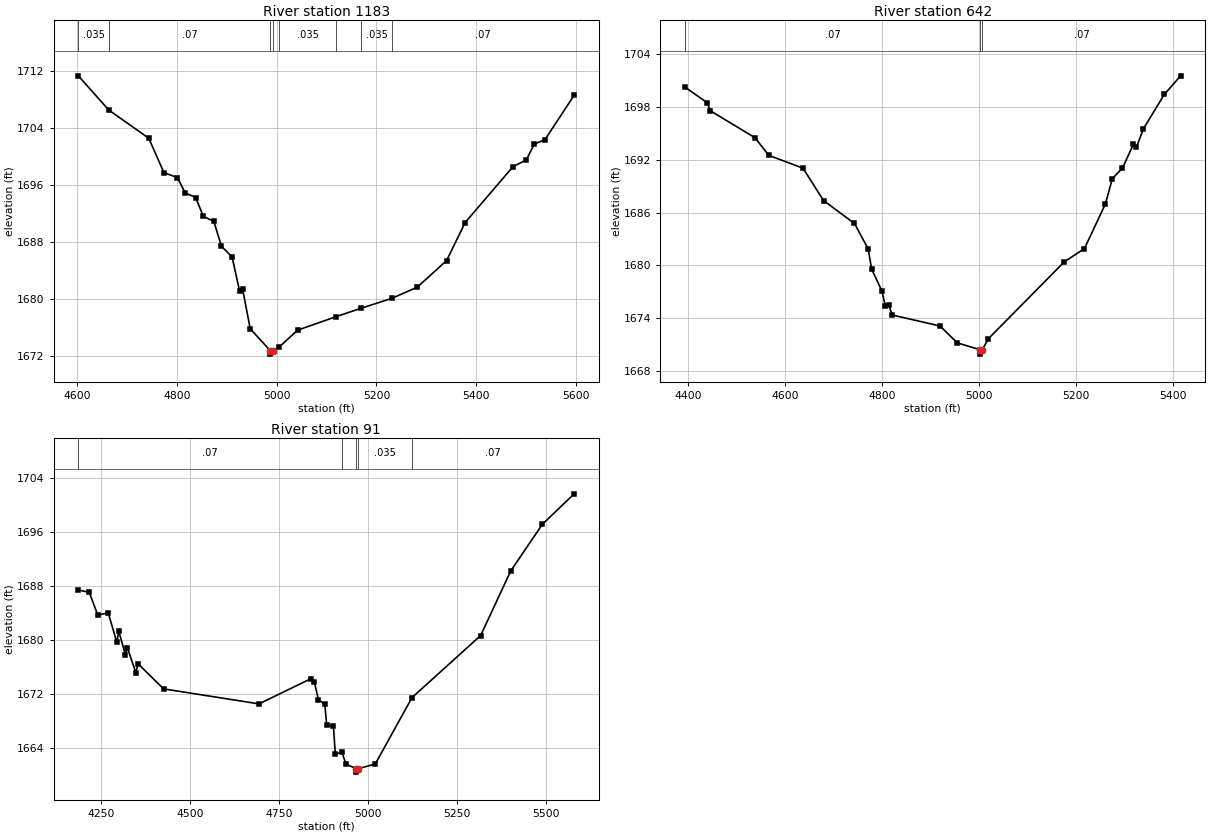
Type RM Length L Ch R = 1,1183,541,541,541
BEGIN DESCRIPTION:
Mapping XS f4e84558
END DESCRIPTION:
XS GIS Cut Line= 3
      1659169.18      6970598.46      1659502.55      6970809.42
      1660019.43      6971113.31
#Sta/Elev= 30
  4602.4 1711.27  4663.3 1706.49  4743.6 1702.54  4774.1 1697.72  4801.2 1697.03
  4816.5 1694.90  4837.7 1694.24  4852.9 1691.62  4874.1 1690.90  4889.4 1687.41
  4910.6 1685.94  4925.8 1681.13  4931.8 1681.41  4947.0 1675.88  4987.1 1672.83
  4987.4 1672.33  4991.8 1672.83  5005.2 1673.33  5041.9 1675.68  5118.3 1677.55
  5169.8 1678.76  5231.3 1680.14  5282.1 1681.71  5340.7 1685.41  5377.8 1690.73
  5473.5 1698.53  5500.8 1699.53  5516.5 1701.72  5537.9 1702.33  5596.5 1708.56
#Mann=8,-1,0
  4602.4   0.035       0  4663.3    0.07       0  4987.1    0.07       0
  4991.8    0.07       0  5005.2   0.035       0  5118.3    0.07       0
  5169.8   0.035       0  5231.3    0.07       0
Bank Sta=4987.1,4991.8
Exp/Cntr=0.3,0.1

Type RM Length L Ch R = 1,642,551,551,551
BEGIN DESCRIPTION:
Mapping XS 66dc4d6a
END DESCRIPTION:
XS GIS Cut Line= 3
      1659181.54      6970886.50      1659603.42      6971318.79
      1659930.75      6971580.31
#Sta/Elev= 30
  4393.4 1700.27  4439.3 1698.50  4446.4 1697.56  4538.3 1694.51  4566.6 1692.51
  4637.3 1691.05  4679.7 1687.37  4743.5 1684.77  4771.8 1681.87  4778.8 1679.60
  4800.1 1677.10  4807.1 1675.41  4814.2 1675.54  4821.2 1674.38  4920.2 1673.12
  4955.5 1671.21  5002.7 1670.43  5003.0 1669.93  5007.4 1670.43  5019.4 1671.66
  5176.3 1680.41  5217.9 1681.91  5261.2 1686.99  5275.6 1689.87  5296.4 1691.06
  5318.8 1693.74  5325.2 1693.43  5339.6 1695.52  5382.9 1699.44  5416.4 1701.54
#Mann=3,-1,0
  4393.4    0.07       0  5002.7    0.07       0  5007.4    0.07       0
Bank Sta=5002.7,5007.4
Exp/Cntr=0.3,0.1

Type RM Length L Ch R = 1,91,0,0,0
BEGIN DESCRIPTION:
Chimney Creek 1145 1.0
END DESCRIPTION:
XS GIS Cut Line= 3
      1659099.14      6971043.34      1659404.94      6971797.06
      1659979.97      6971863.00
#Sta/Elev= 30
  4186.6 1687.42  4217.1 1687.10  4241.1 1683.72  4270.6 1684.02  4294.7 1679.67
  4300.1 1681.31  4318.8 1677.80  4324.2 1678.88  4348.3 1675.11  4353.7 1676.49
  4426.0 1672.74  4693.9 1670.51  4839.1 1674.24  4849.2 1673.79  4860.7 1671.14
  4878.7 1670.48  4884.1 1667.30  4902.8 1667.21  4908.2 1663.06  4927.0 1663.32
  4937.7 1661.60  4966.3 1660.87  4966.6 1660.37  4971.0 1660.87  5020.2 1661.57
  5123.6 1671.45  5316.3 1680.67  5400.5 1690.24  5489.6 1697.20  5578.8 1701.72
#Mann=5,-1,0
  4186.6    0.07       0  4927.0   0.035       0  4966.3   0.035       0
  4971.0   0.035       0  5123.6    0.07       0
Bank Sta=4966.3,4971
Exp/Cntr=0.3,0.1

Chan Stop Cuts=-1