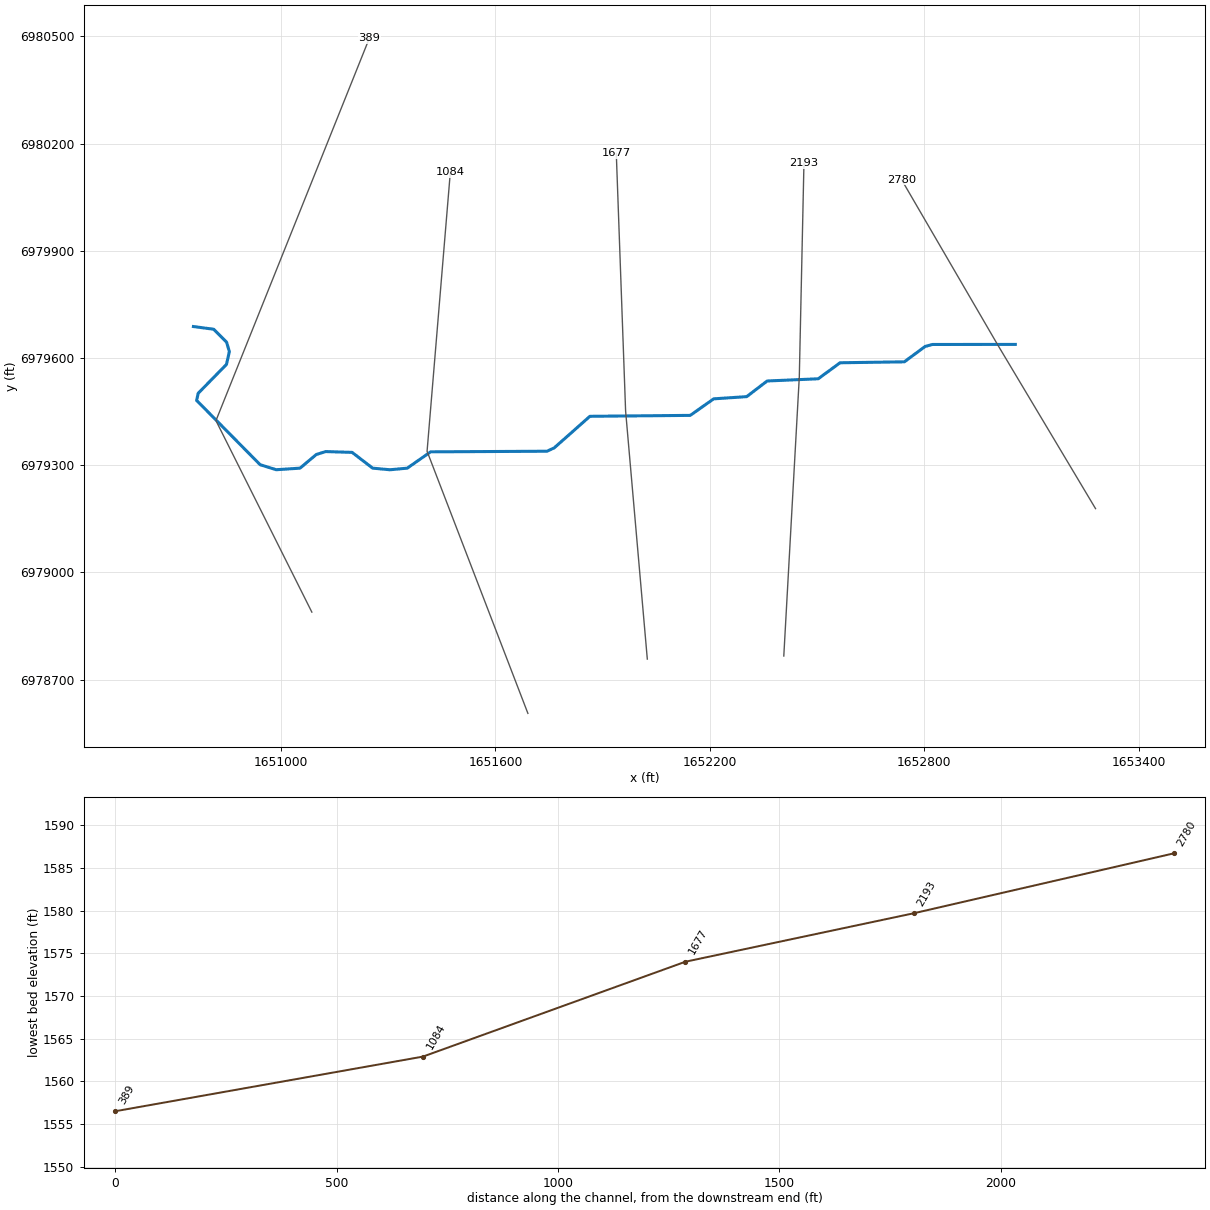
--- Chimney Creek 1146.prj (project) ---

Proj Title=Chimney Creek 1146 Base Level Engineering
Current Plan=p01
Default Exp/Contr=0.3,0.1
English Units
Geom File=g01
Flow File=f01
Plan File=p01
BEGIN DESCRIPTION:
Chimney Creek 1146
END DESCRIPTION:

--- Chimney Creek 1146.p01 (plan) ---

Plan Title=Multiple Run
Short Identifier=Multiple
Geom File=g01
Flow File=f01
Subcritical Flow
K Sum by GR= 0
Std Step Tol= 0.01
Critical Tol= 0.01
Num of Std Step Trials= 20
Max Error Tol= 0.3
Flow Tol Ratio= 0.001
Split Flow NTrial= 30
Split Flow Tol= 0.02
Split Flow Ratio= 0.02
Log Output Level= 0
Friction Slope Method= 1
Unsteady Friction Slope Method= 2
Unsteady Bridges Friction Slope Method= 1
Parabolic Critical Depth
Global Vel Dist=  1 , 1 , 1
Global Log Level= 0
CheckData=True
Encroach Param= -1, 0, 0, 0
BEGIN DESCRIPTION:
Multiple Run
END DESCRIPTION:

--- Chimney Creek 1146.f01 (steady flow) ---

Flow Title=Multiple
Number of Profiles=7
Profile Names=10-year,25-year,50-year,1pct_min,100-year,1pct_plu,500-year
River Rch & RM= Chimney Creek 11,Reach-1,2780
     368     524     658     411     820    1637    1293
Boundary for River Rch & Prof#=Chimney Creek 11,Reach-1,1
Up Type=0
Dn Type=3
Dn Slope=0.005
Boundary for River Rch & Prof#=Chimney Creek 11,Reach-1,2
Up Type=0
Dn Type=3
Dn Slope=0.005
Boundary for River Rch & Prof#=Chimney Creek 11,Reach-1,3
Up Type=0
Dn Type=3
Dn Slope=0.005
Boundary for River Rch & Prof#=Chimney Creek 11,Reach-1,4
Up Type=0
Dn Type=3
Dn Slope=0.005
Boundary for River Rch & Prof#=Chimney Creek 11,Reach-1,5
Up Type=0
Dn Type=3
Dn Slope=0.005
Boundary for River Rch & Prof#=Chimney Creek 11,Reach-1,6
Up Type=0
Dn Type=3
Dn Slope=0.005
Boundary for River Rch & Prof#=Chimney Creek 11,Reach-1,7
Up Type=0
Dn Type=3
Dn Slope=0.005

--- Chimney Creek 1146.g01 (geometry) ---

Geom Title=Existing Conditions

River Reach=Chimney Creek 11,Reach-1
Reach XY= 30
      1653055.00      6979638.00      1652823.27      6979637.79
      1652802.67      6979632.25      1652744.49      6979589.22
      1652564.66      6979586.62      1652503.43      6979541.79
      1652360.53      6979535.61      1652303.40      6979491.86
      1652210.98      6979485.64      1652145.34      6979439.38
      1651864.59      6979436.79      1651764.79      6979348.50
      1651744.56      6979339.06      1651418.92      6979337.31
      1651353.40      6979291.70      1651305.00      6979287.18
      1651256.60      6979291.71      1651199.03      6979335.83
      1651125.10      6979338.09      1651098.96      6979329.90
      1651053.40      6979291.70      1650986.73      6979287.29
      1650941.70      6979301.34      1650763.96      6979481.33
      1650768.44      6979501.32      1650847.51      6979581.96
      1650855.56      6979617.90      1650847.81      6979644.30
      1650811.77      6979680.41      1650755.00      6979688.00

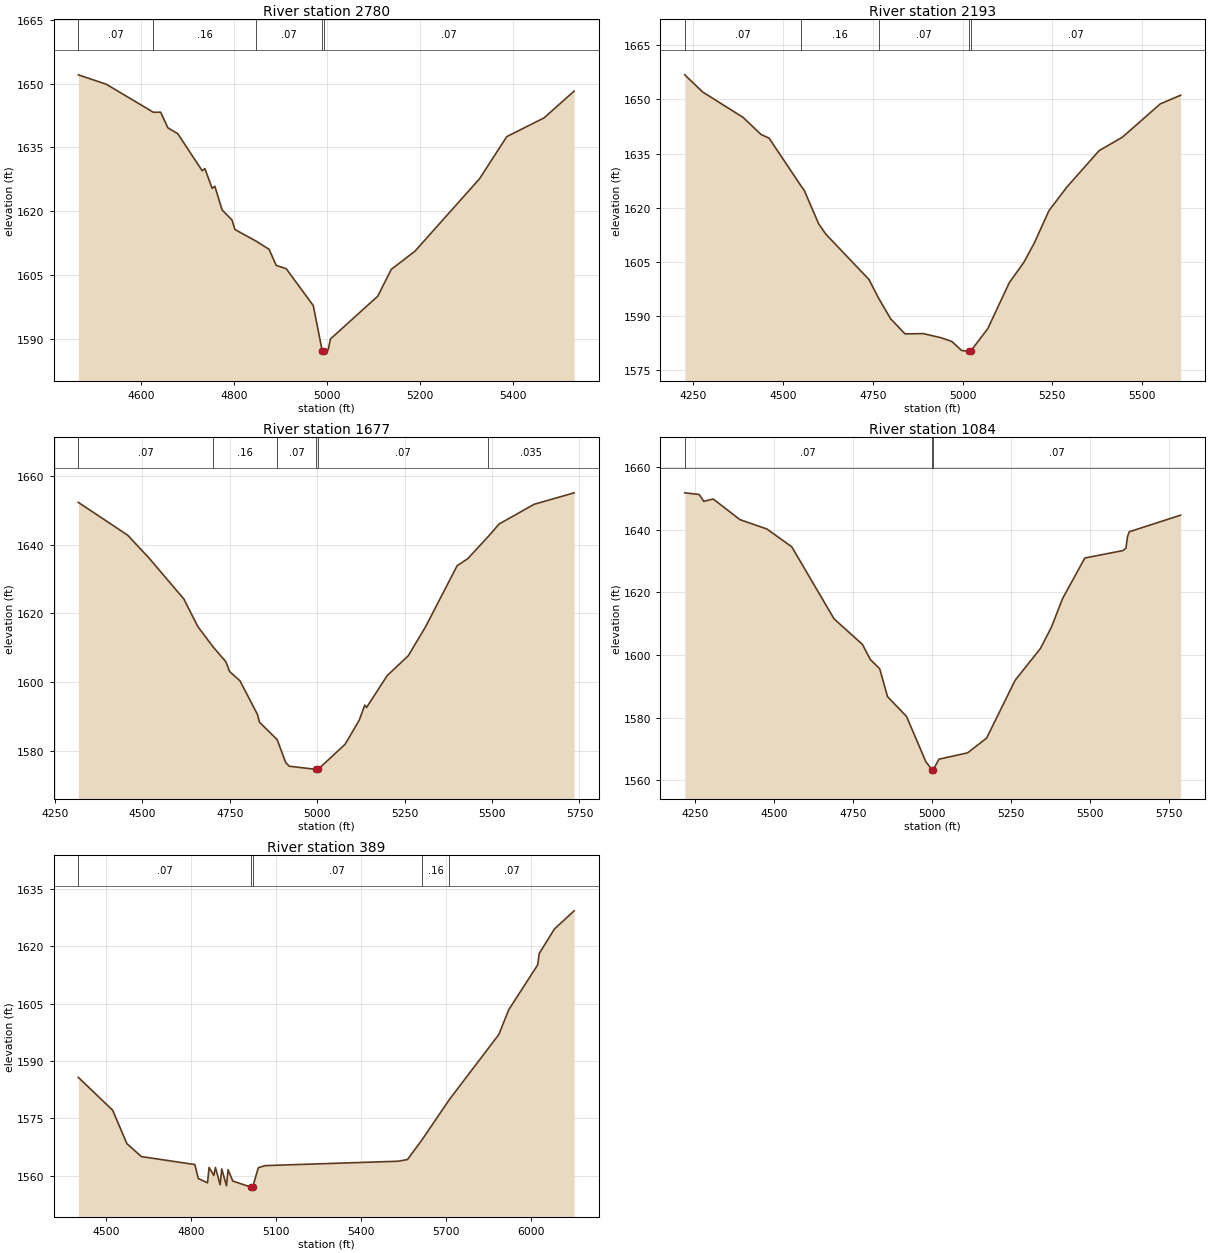
Type RM Length L Ch R = 1,2780,587,587,587
BEGIN DESCRIPTION:
Chimney Creek 1146 5.0
END DESCRIPTION:
XS GIS Cut Line= 3
      1653279.56      6979178.39      1653005.00      6979638.00
      1652737.03      6980098.53
#Sta/Elev= 30
  4464.6 1652.07  4525.2 1649.84  4626.3 1643.27  4642.0 1643.29  4657.5 1639.62
  4678.9 1638.23  4731.5 1629.52  4737.3 1630.04  4752.9 1625.40  4758.7 1625.90
  4774.3 1620.34  4795.7 1617.95  4802.0 1615.73  4847.4 1613.01  4875.5 1611.08
  4891.0 1607.29  4912.4 1606.53  4970.8 1597.84  4990.1 1587.18  4990.4 1586.68
  4994.2 1587.18  5002.9 1587.50  5007.8 1590.01  5109.6 1600.05  5138.8 1606.36
  5189.9 1610.64  5328.9 1627.64  5387.6 1637.55  5467.9 1641.95  5532.8 1648.25
#Mann=5,-1,0
  4464.6    0.07       0  4626.3    0.16       0  4847.4    0.07       0
  4990.1    0.07       0  4994.2    0.07       0
Bank Sta=4990.1,4994.2
Exp/Cntr=0.3,0.1

Type RM Length L Ch R = 1,2193,516,516,516
BEGIN DESCRIPTION:
Mapping XS cfa6eda3
END DESCRIPTION:
XS GIS Cut Line= 3
      1652407.15      6978766.04      1652450.56      6979547.33
      1652463.54      6980144.60
#Sta/Elev= 30
  4227.1 1656.83  4276.3 1652.11  4389.3 1645.03  4439.4 1640.29  4461.6 1639.28
  4550.0 1626.12  4559.6 1624.78  4599.6 1615.54  4619.7 1612.65  4739.8 1600.08
  4766.4 1594.92  4799.9 1589.21  4840.0 1585.01  4890.1 1585.10  4940.2 1583.95
  4970.2 1582.92  4997.4 1580.42  5018.2 1580.18  5018.5 1579.68  5022.3 1580.18
  5070.3 1586.47  5130.3 1599.23  5170.3 1604.78  5200.3 1610.30  5240.3 1619.13
  5290.3 1625.71  5380.4 1635.83  5444.7 1639.52  5550.4 1648.78  5607.0 1651.17
#Mann=5,-1,0
  4227.1    0.07       0  4550.0    0.16       0  4766.4    0.07       0
  5018.2    0.07       0  5022.3    0.07       0
Bank Sta=5018.2,5022.3
Exp/Cntr=0.3,0.1

Type RM Length L Ch R = 1,1677,593,593,593
BEGIN DESCRIPTION:
Mapping XS b2ebdd12
END DESCRIPTION:
XS GIS Cut Line= 3
      1652025.21      6978757.37      1651964.45      6979451.84
      1651938.40      6980172.35
#Sta/Elev= 30
  4316.7 1652.40  4457.9 1642.82  4518.1 1636.25  4618.5 1624.22  4658.6 1616.16
  4702.2 1610.23  4738.9 1605.89  4749.0 1603.10  4779.1 1600.34  4829.3 1590.48
  4834.8 1588.28  4885.4 1583.20  4909.6 1576.56  4919.6 1575.45  4997.6 1574.51
  4998.0 1574.01  5002.2 1574.51  5080.0 1581.88  5120.1 1588.87  5136.0 1593.27
  5141.0 1592.56  5200.1 1601.88  5260.1 1607.63  5310.2 1616.19  5400.2 1633.93
  5430.3 1635.96  5489.7 1642.51  5520.3 1646.10  5620.4 1651.84  5734.8 1655.18
#Mann=6,-1,0
  4316.7    0.07       0  4702.2    0.16       0  4885.4    0.07       0
  4997.6    0.07       0  5002.2    0.07       0  5489.7   0.035       0
Bank Sta=4997.6,5002.2
Exp/Cntr=0.3,0.1

Type RM Length L Ch R = 1,1084,695,695,695
BEGIN DESCRIPTION:
Mapping XS 60626cfa
END DESCRIPTION:
XS GIS Cut Line= 3
      1651691.02      6978605.45      1651408.89      6979339.00
      1651474.00      6980120.26
#Sta/Elev= 30
  4217.8 1651.72  4263.4 1651.19  4277.9 1649.00  4307.9 1649.75  4392.6 1643.15
  4477.7 1640.18  4556.5 1634.49  4690.4 1611.51  4780.4 1603.33  4805.0 1598.56
  4835.0 1595.57  4859.7 1586.68  4919.7 1580.39  4981.2 1565.89  4999.9 1563.41
  5000.2 1562.91  5004.5 1563.41  5022.8 1566.73  5113.1 1568.74  5173.3 1573.44
  5263.6 1591.88  5343.9 1602.06  5378.7 1608.87  5414.2 1618.04  5484.4 1630.92
  5604.8 1633.29  5614.5 1634.04  5619.5 1637.71  5624.9 1639.29  5787.7 1644.59
#Mann=3,-1,0
  4217.8    0.07       0  4999.9    0.07       0  5004.5    0.07       0
Bank Sta=4999.9,5004.5
Exp/Cntr=0.3,0.1

Type RM Length L Ch R = 1,389,0,0,0
BEGIN DESCRIPTION:
Chimney Creek 1146 1.0
END DESCRIPTION:
XS GIS Cut Line= 3
      1651086.38      6978888.89      1650818.09      6979424.67
      1651247.21      6980494.51
#Sta/Elev= 30
  4400.8 1585.76  4522.0 1577.17  4572.3 1568.43  4623.5 1565.03  4812.5 1562.95
  4824.8 1559.30  4857.2 1558.17  4862.8 1562.20  4879.6 1560.09  4885.2 1562.20
  4901.9 1557.67  4907.5 1561.81  4924.3 1557.42  4929.9 1561.60  4946.6 1558.63
  5012.0 1557.02  5012.3 1556.52  5016.8 1557.02  5036.6 1562.12  5060.9 1562.67
  5531.5 1563.82  5563.9 1564.27  5614.4 1569.34  5711.7 1579.94  5886.6 1596.97
  5921.6 1603.45  6023.8 1615.17  6029.2 1618.15  6083.0 1624.57  6152.7 1629.32
#Mann=5,-1,0
  4400.8    0.07       0  5012.0    0.07       0  5016.8    0.07       0
  5614.4    0.16       0  5711.7    0.07       0
Bank Sta=5012,5016.8
Exp/Cntr=0.3,0.1

Chan Stop Cuts=-1