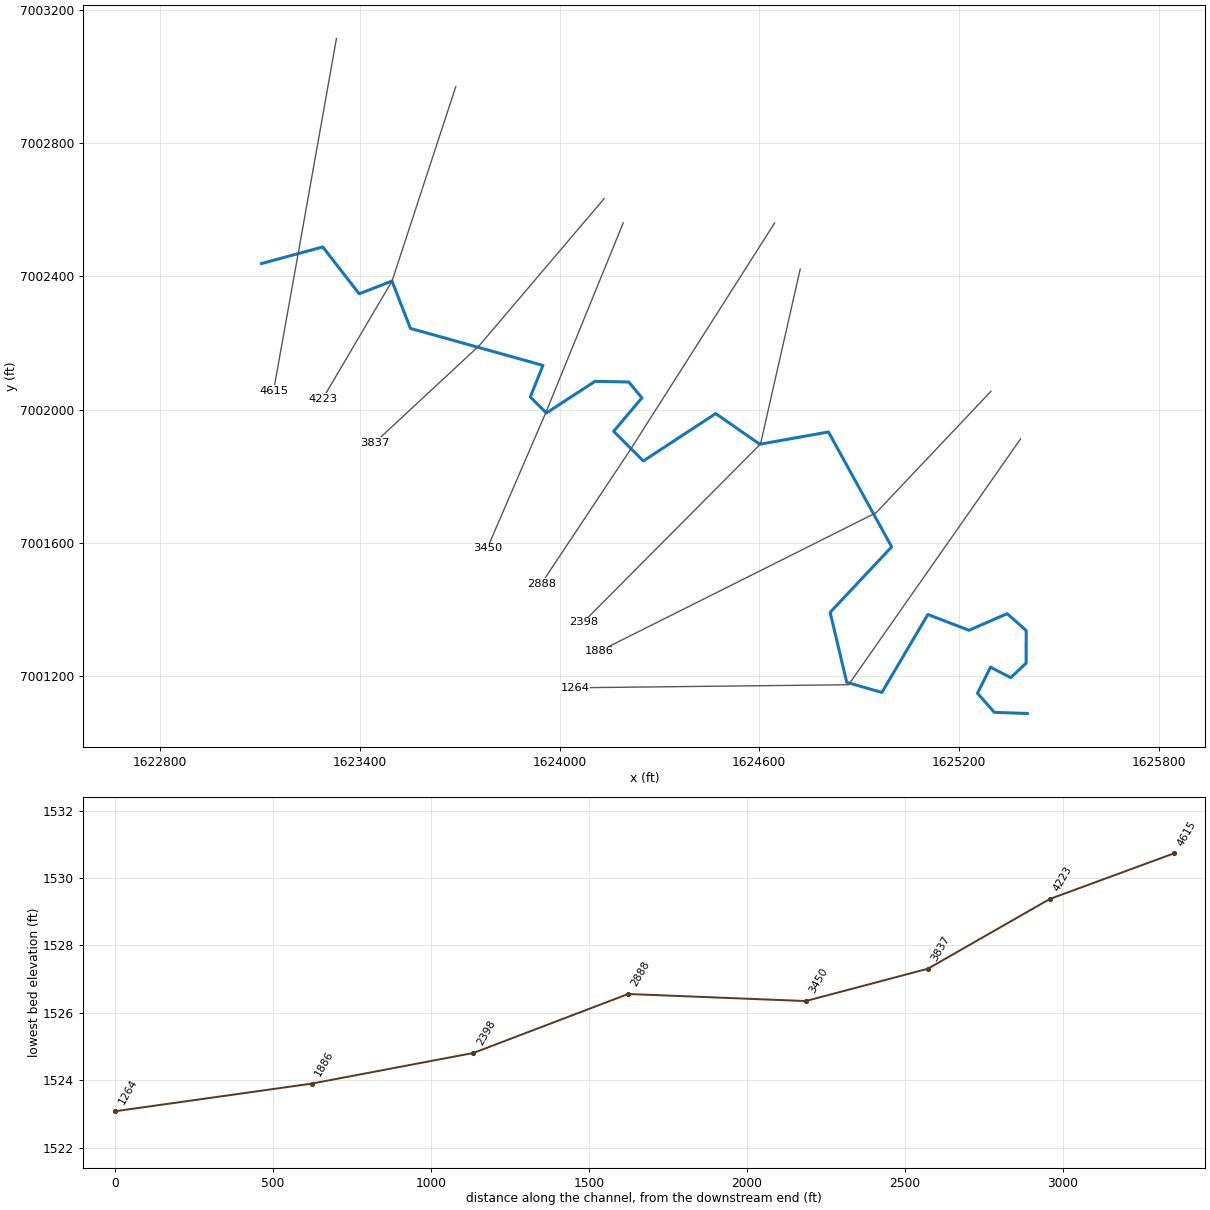
--- Chimney Creek 1149.prj (project) ---

Proj Title=Chimney Creek 1149 Base Level Engineering
Current Plan=p01
Default Exp/Contr=0.3,0.1
English Units
Geom File=g01
Flow File=f01
Plan File=p01
BEGIN DESCRIPTION:
Chimney Creek 1149
END DESCRIPTION:

--- Chimney Creek 1149.p01 (plan) ---

Plan Title=Multiple Run
Short Identifier=Multiple
Geom File=g01
Flow File=f01
Subcritical Flow
K Sum by GR= 0
Std Step Tol= 0.01
Critical Tol= 0.01
Num of Std Step Trials= 20
Max Error Tol= 0.3
Flow Tol Ratio= 0.001
Split Flow NTrial= 30
Split Flow Tol= 0.02
Split Flow Ratio= 0.02
Log Output Level= 0
Friction Slope Method= 1
Unsteady Friction Slope Method= 2
Unsteady Bridges Friction Slope Method= 1
Parabolic Critical Depth
Global Vel Dist=  1 , 1 , 1
Global Log Level= 0
CheckData=True
Encroach Param= -1, 0, 0, 0
BEGIN DESCRIPTION:
Multiple Run
END DESCRIPTION:

--- Chimney Creek 1149.f01 (steady flow) ---

Flow Title=Multiple
Number of Profiles=7
Profile Names=10-year,25-year,50-year,1pct_min,100-year,1pct_plu,500-year
River Rch & RM= Chimney Creek 11,Reach-1,4615
     185     249     299     179     358     714     518
River Rch & RM= Chimney Creek 11,Reach-1,4223
     248     338     412     250     498     993     737
Boundary for River Rch & Prof#=Chimney Creek 11,Reach-1,1
Up Type=0
Dn Type=3
Dn Slope=0.005
Boundary for River Rch & Prof#=Chimney Creek 11,Reach-1,2
Up Type=0
Dn Type=3
Dn Slope=0.005
Boundary for River Rch & Prof#=Chimney Creek 11,Reach-1,3
Up Type=0
Dn Type=3
Dn Slope=0.005
Boundary for River Rch & Prof#=Chimney Creek 11,Reach-1,4
Up Type=0
Dn Type=3
Dn Slope=0.005
Boundary for River Rch & Prof#=Chimney Creek 11,Reach-1,5
Up Type=0
Dn Type=3
Dn Slope=0.005
Boundary for River Rch & Prof#=Chimney Creek 11,Reach-1,6
Up Type=0
Dn Type=3
Dn Slope=0.005
Boundary for River Rch & Prof#=Chimney Creek 11,Reach-1,7
Up Type=0
Dn Type=3
Dn Slope=0.005

--- Chimney Creek 1149.g01 (geometry) ---

Geom Title=Existing Conditions

River Reach=Chimney Creek 11,Reach-1
Reach XY= 30
      1623105.00      7002438.00      1623288.99      7002487.78
      1623398.27      7002347.15      1623496.83      7002385.46
      1623552.27      7002243.35      1623950.21      7002132.41
      1623912.27      7002037.66      1623960.65      7001989.58
      1624106.51      7002084.53      1624208.00      7002082.60
      1624247.47      7002034.88      1624162.61      7001934.64
      1624251.63      7001845.60      1624469.12      7001987.83
      1624601.59      7001895.81      1624807.70      7001932.65
      1624997.71      7001587.91      1624812.79      7001391.42
      1624862.70      7001181.43      1624968.23      7001151.09
      1625106.39      7001384.97      1625230.00      7001337.62
      1625344.55      7001387.47      1625401.63      7001336.77
      1625401.54      7001239.03      1625355.23      7001195.47
      1625294.57      7001226.88      1625255.46      7001148.57
      1625306.08      7001091.28      1625405.00      7001088.00

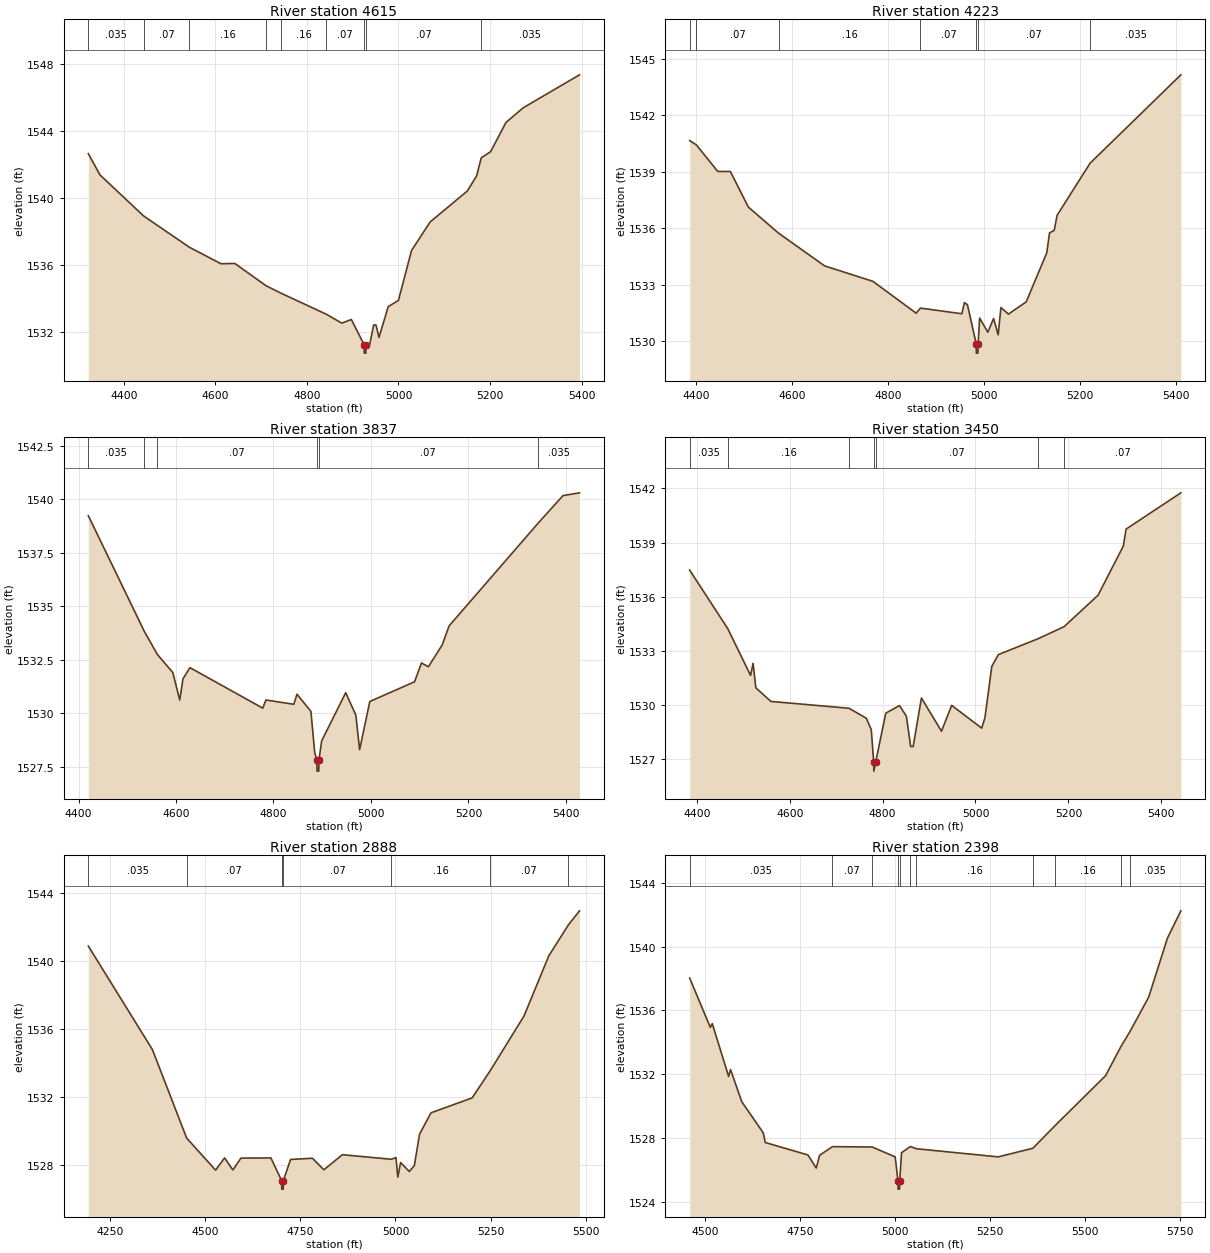
Type RM Length L Ch R = 1,4615,392,392,392
BEGIN DESCRIPTION:
Chimney Creek 1149 6.0
END DESCRIPTION:
XS GIS Cut Line= 3
      1623330.00      7003112.98      1623211.14      7002446.19
      1623141.24      7002056.91
#Sta/Elev= 30
  4322.7 1542.65  4348.1 1541.38  4443.3 1538.93  4543.2 1537.06  4612.4 1536.07
  4642.6 1536.09  4710.7 1534.76  4742.9 1534.32  4842.8 1533.05  4876.3 1532.52
  4897.1 1532.74  4925.1 1531.23  4925.3 1530.73  4928.8 1530.73  4929.1 1531.23
  4937.2 1531.25  4945.9 1532.41  4951.0 1532.41  4957.5 1531.67  4977.8 1533.51
  5000.0 1533.88  5028.6 1536.86  5069.3 1538.57  5150.6 1540.42  5170.9 1541.33
  5180.9 1542.40  5201.4 1542.77  5234.8 1544.51  5272.5 1545.39  5395.5 1547.36
#Mann=9,-1,0
  4322.7   0.035       0  4443.3    0.07       0  4543.2    0.16       0
  4710.7    0.07       0  4742.9    0.16       0  4842.8    0.07       0
  4925.1    0.07       0  4929.1    0.07       0  5180.9   0.035       0
Bank Sta=4925.1,4929.1
Exp/Cntr=0.3,0.1

Type RM Length L Ch R = 1,4223,386,386,386
BEGIN DESCRIPTION:
Mapping XS cc0b2e08
END DESCRIPTION:
XS GIS Cut Line= 3
      1623688.37      7002968.66      1623496.97      7002385.34
      1623288.24      7002031.42
#Sta/Elev= 30
  4386.1 1540.66  4400.1 1540.43  4444.8 1539.02  4471.0 1539.02  4508.5 1537.13
  4571.4 1535.75  4667.6 1534.01  4768.4 1533.19  4858.6 1531.50  4867.6 1531.77
  4954.0 1531.47  4959.3 1532.06  4965.6 1531.95  4983.9 1529.88  4984.1 1529.38
  4987.6 1529.38  4987.9 1529.88  4991.1 1531.24  5008.2 1530.49  5020.2 1531.22
  5029.7 1530.35  5035.5 1531.80  5051.1 1531.45  5088.2 1532.10  5131.1 1534.70
  5136.9 1535.76  5146.8 1535.90  5152.6 1536.69  5221.5 1539.46  5410.9 1544.15
#Mann=7,-1,0
  4386.1   0.035       0  4400.1    0.07       0  4571.4    0.16       0
  4867.6    0.07       0  4983.9    0.07       0  4987.9    0.07       0
  5221.5   0.035       0
Bank Sta=4983.9,4987.9
Exp/Cntr=0.3,0.1

Type RM Length L Ch R = 1,3837,387,387,387
BEGIN DESCRIPTION:
Mapping XS 8359ba31
END DESCRIPTION:
XS GIS Cut Line= 3
      1624134.06      7002632.85      1623759.08      7002191.90
      1623444.82      7001900.21
#Sta/Elev= 30
  4420.2 1539.23  4535.3 1533.82  4562.0 1532.75  4593.5 1531.91  4607.7 1530.63
  4614.3 1531.62  4628.6 1532.14  4778.0 1530.25  4784.5 1530.63  4841.7 1530.43
  4848.2 1530.90  4876.8 1530.10  4884.5 1528.19  4889.0 1527.81  4889.3 1527.31
  4892.9 1527.31  4893.2 1527.81  4898.8 1528.72  4948.2 1530.97  4969.0 1529.92
  4976.7 1528.31  4997.6 1530.56  5089.4 1531.48  5103.6 1532.36  5117.8 1532.18
  5146.1 1533.20  5160.3 1534.09  5342.0 1538.86  5393.9 1540.17  5427.8 1540.30
#Mann=6,-1,0
  4420.2   0.035       0  4535.3    0.16       0  4562.0    0.07       0
  4889.0    0.07       0  4893.2    0.07       0  5342.0   0.035       0
Bank Sta=4889,4893.2
Exp/Cntr=0.3,0.1

Type RM Length L Ch R = 1,3450,562,562,562
BEGIN DESCRIPTION:
Mapping XS 44dbbe4b
END DESCRIPTION:
XS GIS Cut Line= 3
      1624191.37      7002559.95      1623958.73      7001990.51
      1623783.38      7001584.27
#Sta/Elev= 30
  4384.6 1537.48  4466.8 1534.23  4515.7 1531.65  4521.1 1532.32  4527.1 1530.96
  4559.5 1530.21  4727.7 1529.83  4764.8 1529.28  4775.6 1528.65  4780.8 1526.85
  4781.1 1526.35  4785.0 1526.85  4806.9 1529.56  4836.4 1529.98  4851.2 1529.39
  4860.4 1527.72  4865.8 1527.71  4883.6 1530.40  4926.8 1528.56  4948.7 1529.99
  5013.4 1528.73  5020.3 1529.30  5035.1 1532.15  5049.2 1532.80  5135.6 1533.69
  5190.8 1534.35  5263.9 1536.09  5318.3 1538.81  5324.2 1539.75  5442.2 1541.76
#Mann=7,-1,0
  4384.6   0.035       0  4466.8    0.16       0  4727.7    0.07       0
  4780.8    0.07       0  4785.0    0.07       0  5135.6    0.16       0
  5190.8    0.07       0
Bank Sta=4780.8,4785
Exp/Cntr=0.3,0.1

Type RM Length L Ch R = 1,2888,490,490,490
BEGIN DESCRIPTION:
Mapping XS 8016de97
END DESCRIPTION:
XS GIS Cut Line= 3
      1624646.22      7002559.94      1624213.94      7001881.13
      1623944.84      7001476.62
#Sta/Elev= 30
  4193.0 1540.89  4361.3 1534.79  4451.3 1529.57  4527.3 1527.68  4551.0 1528.40
  4572.8 1527.69  4594.0 1528.39  4672.7 1528.40  4700.9 1527.06  4701.3 1526.56
  4705.1 1526.56  4705.4 1527.06  4724.4 1528.31  4781.9 1528.38  4811.8 1527.70
  4860.6 1528.59  4989.2 1528.32  5001.3 1528.42  5006.2 1527.27  5013.5 1528.13
  5036.3 1527.60  5049.6 1527.95  5063.3 1529.80  5093.4 1531.06  5201.6 1531.94
  5249.2 1533.55  5337.8 1536.77  5403.0 1540.32  5454.1 1542.13  5483.6 1542.97
#Mann=7,-1,0
  4193.0   0.035       0  4451.3    0.07       0  4700.9    0.07       0
  4705.4    0.07       0  4989.2    0.16       0  5249.2    0.07       0
  5454.1   0.035       0
Bank Sta=4700.9,4705.4
Exp/Cntr=0.3,0.1

Type RM Length L Ch R = 1,2398,512,512,512
BEGIN DESCRIPTION:
Mapping XS 86bac546
END DESCRIPTION:
XS GIS Cut Line= 3
      1624723.03      7002421.61      1624603.67      7001896.41
      1624071.23      7001361.81
#Sta/Elev= 30
  4460.3 1538.03  4514.6 1534.94  4519.7 1535.18  4562.8 1531.87  4567.9 1532.30
  4597.3 1530.29  4654.1 1528.33  4659.2 1527.73  4771.6 1526.95  4793.5 1526.13
  4802.4 1526.93  4836.1 1527.47  4940.7 1527.45  5001.3 1526.83  5008.7 1525.31
  5009.0 1524.81  5012.9 1524.81  5013.2 1525.31  5018.0 1527.09  5041.3 1527.48
  5057.0 1527.34  5272.6 1526.83  5363.8 1527.37  5422.3 1528.79  5555.4 1531.92
  5595.9 1533.75  5618.7 1534.65  5668.6 1536.83  5718.1 1540.53  5753.4 1542.24
#Mann=11,-1,0
  4460.3   0.035       0  4836.1    0.07       0  4940.7    0.16       0
  5008.7    0.07       0  5013.2    0.16       0  5041.3    0.07       0
  5057.0    0.16       0  5363.8    0.07       0  5422.3    0.16       0
  5595.9    0.07       0  5618.7   0.035       0
Bank Sta=5008.7,5013.2
Exp/Cntr=0.3,0.1

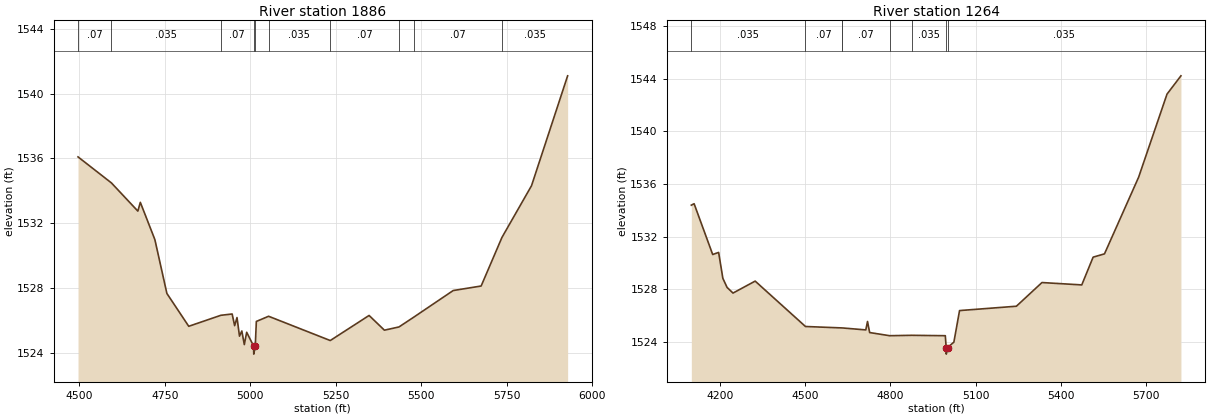
Type RM Length L Ch R = 1,1886,622,622,622
BEGIN DESCRIPTION:
Mapping XS ed545f3f
END DESCRIPTION:
XS GIS Cut Line= 3
      1625295.91      7002054.80      1624950.89      7001690.25
      1624118.74      7001274.18
#Sta/Elev= 30
  4496.3 1536.09  4594.1 1534.48  4671.3 1532.74  4678.6 1533.28  4721.1 1530.98
  4756.3 1527.65  4820.2 1525.62  4914.2 1526.30  4947.2 1526.38  4954.5 1525.66
  4961.4 1526.16  4968.7 1525.01  4975.5 1525.33  4982.8 1524.49  4989.7 1525.25
  5010.0 1524.40  5010.4 1523.90  5014.8 1524.40  5018.0 1525.92  5053.8 1526.24
  5234.2 1524.74  5347.8 1526.29  5392.6 1525.38  5435.3 1525.58  5478.2 1526.18
  5593.8 1527.83  5675.6 1528.11  5736.4 1531.11  5823.0 1534.31  5928.6 1541.10
#Mann=10,-1,0
  4496.3    0.07       0  4594.1   0.035       0  4914.2    0.07       0
  5010.0    0.07       0  5014.8    0.07       0  5053.8   0.035       0
  5234.2    0.07       0  5435.3    0.16       0  5478.2    0.07       0
  5736.4   0.035       0
Bank Sta=5010,5014.8
Exp/Cntr=0.3,0.1

Type RM Length L Ch R = 1,1264,0,0,0
BEGIN DESCRIPTION:
Chimney Creek 1149 1.0
END DESCRIPTION:
XS GIS Cut Line= 3
      1625384.93      7001912.06      1624868.23      7001174.19
      1624045.98      7001165.08
#Sta/Elev= 30
  4099.2 1534.40  4109.0 1534.51  4174.4 1530.65  4195.3 1530.81  4210.2 1528.84
  4225.0 1528.15  4245.9 1527.72  4323.9 1528.63  4500.9 1525.18  4631.0 1525.07
  4631.1 1525.07  4713.2 1524.92  4719.3 1525.56  4726.8 1524.72  4797.1 1524.48
  4874.6 1524.51  4993.1 1524.48  4996.1 1523.58  4996.4 1523.08  5000.9 1523.58
  5023.2 1523.99  5043.2 1526.39  5243.2 1526.72  5333.2 1528.52  5473.3 1528.34
  5513.3 1530.45  5553.3 1530.70  5673.3 1536.52  5773.3 1542.84  5822.3 1544.23
#Mann=8,-1,0
  4099.2   0.035       0  4500.9    0.07       0  4631.0    0.16       0
  4631.1    0.07       0  4797.1    0.16       0  4874.6   0.035       0
  4996.1   0.035       0  5000.9   0.035       0
Bank Sta=4996.1,5000.9
Exp/Cntr=0.3,0.1

Chan Stop Cuts=-1