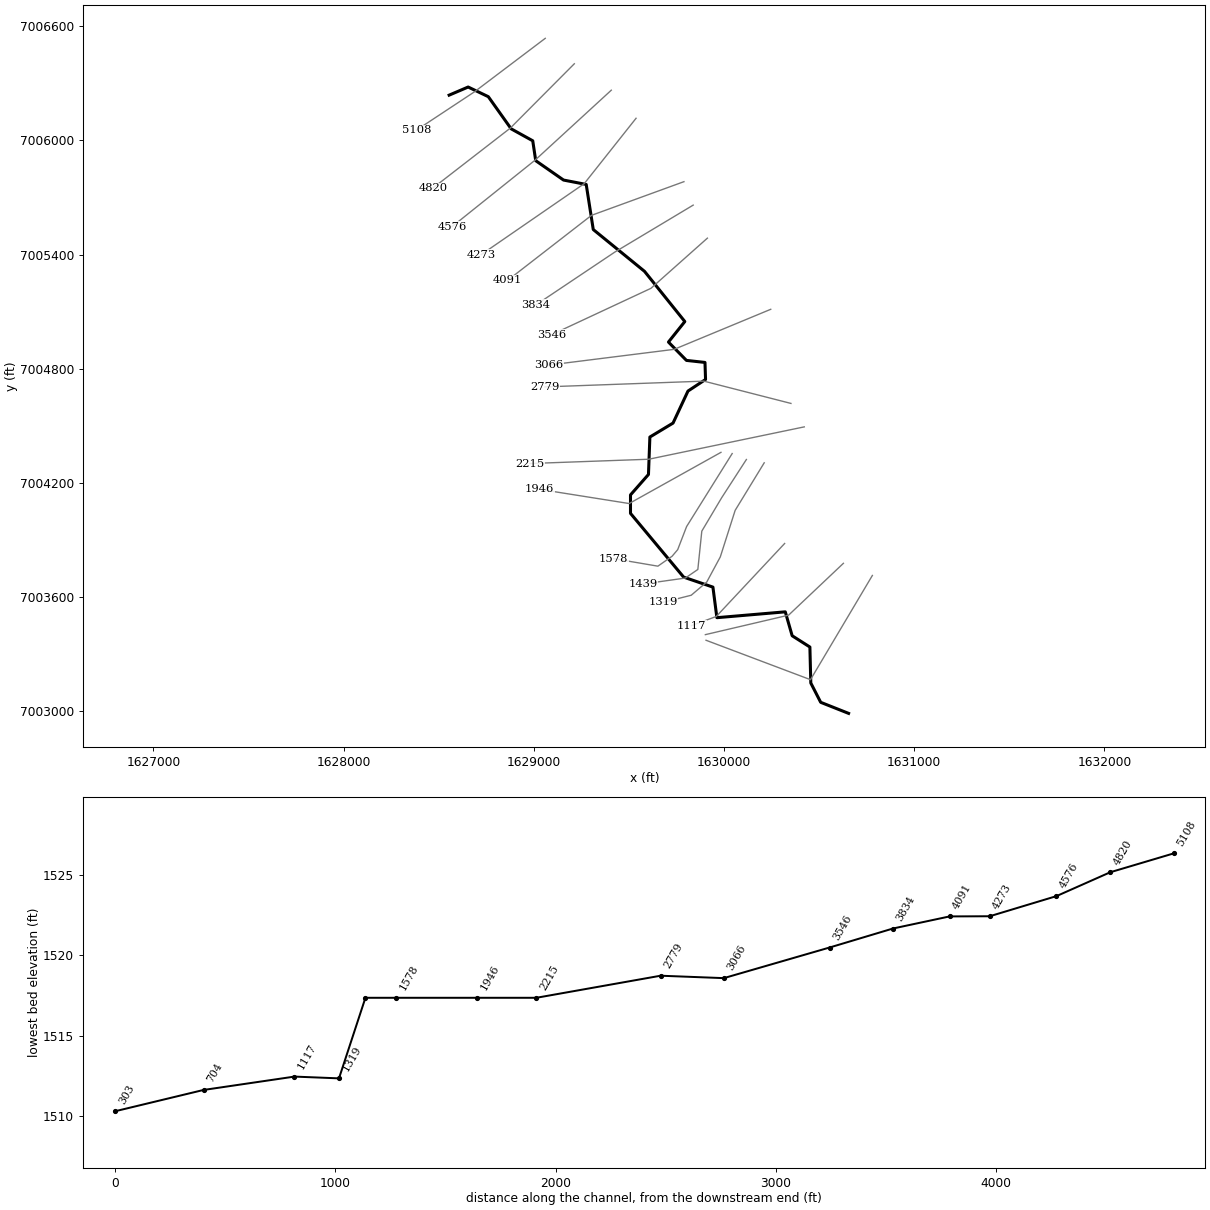
--- Chimney Creek 1150.prj (project) ---

Proj Title=Chimney Creek 1150 Base Level Engineering
Current Plan=p01
Default Exp/Contr=0.3,0.1
English Units
Geom File=g01
Flow File=f01
Plan File=p01
BEGIN DESCRIPTION:
Chimney Creek 1150
END DESCRIPTION:

--- Chimney Creek 1150.p01 (plan) ---

Plan Title=Multiple Run
Short Identifier=Multiple
Geom File=g01
Flow File=f01
Subcritical Flow
K Sum by GR= 0
Std Step Tol= 0.01
Critical Tol= 0.01
Num of Std Step Trials= 20
Max Error Tol= 0.3
Flow Tol Ratio= 0.001
Split Flow NTrial= 30
Split Flow Tol= 0.02
Split Flow Ratio= 0.02
Log Output Level= 0
Friction Slope Method= 1
Unsteady Friction Slope Method= 2
Unsteady Bridges Friction Slope Method= 1
Parabolic Critical Depth
Global Vel Dist=  1 , 1 , 1
Global Log Level= 0
CheckData=True
Encroach Param= -1, 0, 0, 0
BEGIN DESCRIPTION:
Multiple Run
END DESCRIPTION:

--- Chimney Creek 1150.f01 (steady flow) ---

Flow Title=Multiple
Number of Profiles=7
Profile Names=10-year,25-year,50-year,1pct_min,100-year,1pct_plu,500-year
River Rch & RM= Chimney Creek 11,Reach-1,5108
     213     290     353     214     427     852     632
River Rch & RM= Chimney Creek 11,Reach-1,4091
     227     309     375     227     452     903     667
Boundary for River Rch & Prof#=Chimney Creek 11,Reach-1,1
Up Type=0
Dn Type=3
Dn Slope=0.005
Boundary for River Rch & Prof#=Chimney Creek 11,Reach-1,2
Up Type=0
Dn Type=3
Dn Slope=0.005
Boundary for River Rch & Prof#=Chimney Creek 11,Reach-1,3
Up Type=0
Dn Type=3
Dn Slope=0.005
Boundary for River Rch & Prof#=Chimney Creek 11,Reach-1,4
Up Type=0
Dn Type=3
Dn Slope=0.005
Boundary for River Rch & Prof#=Chimney Creek 11,Reach-1,5
Up Type=0
Dn Type=3
Dn Slope=0.005
Boundary for River Rch & Prof#=Chimney Creek 11,Reach-1,6
Up Type=0
Dn Type=3
Dn Slope=0.005
Boundary for River Rch & Prof#=Chimney Creek 11,Reach-1,7
Up Type=0
Dn Type=3
Dn Slope=0.005

--- Chimney Creek 1150.g01 (geometry) ---

Geom Title=Existing Conditions

River Reach=Chimney Creek 11,Reach-1
Reach XY= 30
      1628555.00      7006238.00      1628654.97      7006280.72
      1628761.07      7006229.89      1628881.17      7006060.86
      1628994.60      7005998.06      1629010.26      7005893.47
      1629156.50      7005791.63      1629275.65      7005768.58
      1629312.74      7005531.54      1629582.14      7005311.83
      1629794.06      7005047.87      1629707.95      7004940.00
      1629802.62      7004843.55      1629900.05      7004832.89
      1629903.02      7004743.40      1629810.63      7004682.38
      1629732.14      7004514.16      1629610.36      7004440.70
      1629602.93      7004243.86      1629508.47      7004136.50
      1629508.46      7004039.50      1629787.87      7003704.30
      1629941.80      7003651.73      1629962.62      7003491.07
      1630322.20      7003521.78      1630358.35      7003396.06
      1630451.52      7003336.74      1630456.35      7003147.63
      1630508.36      7003046.13      1630655.00      7002988.00

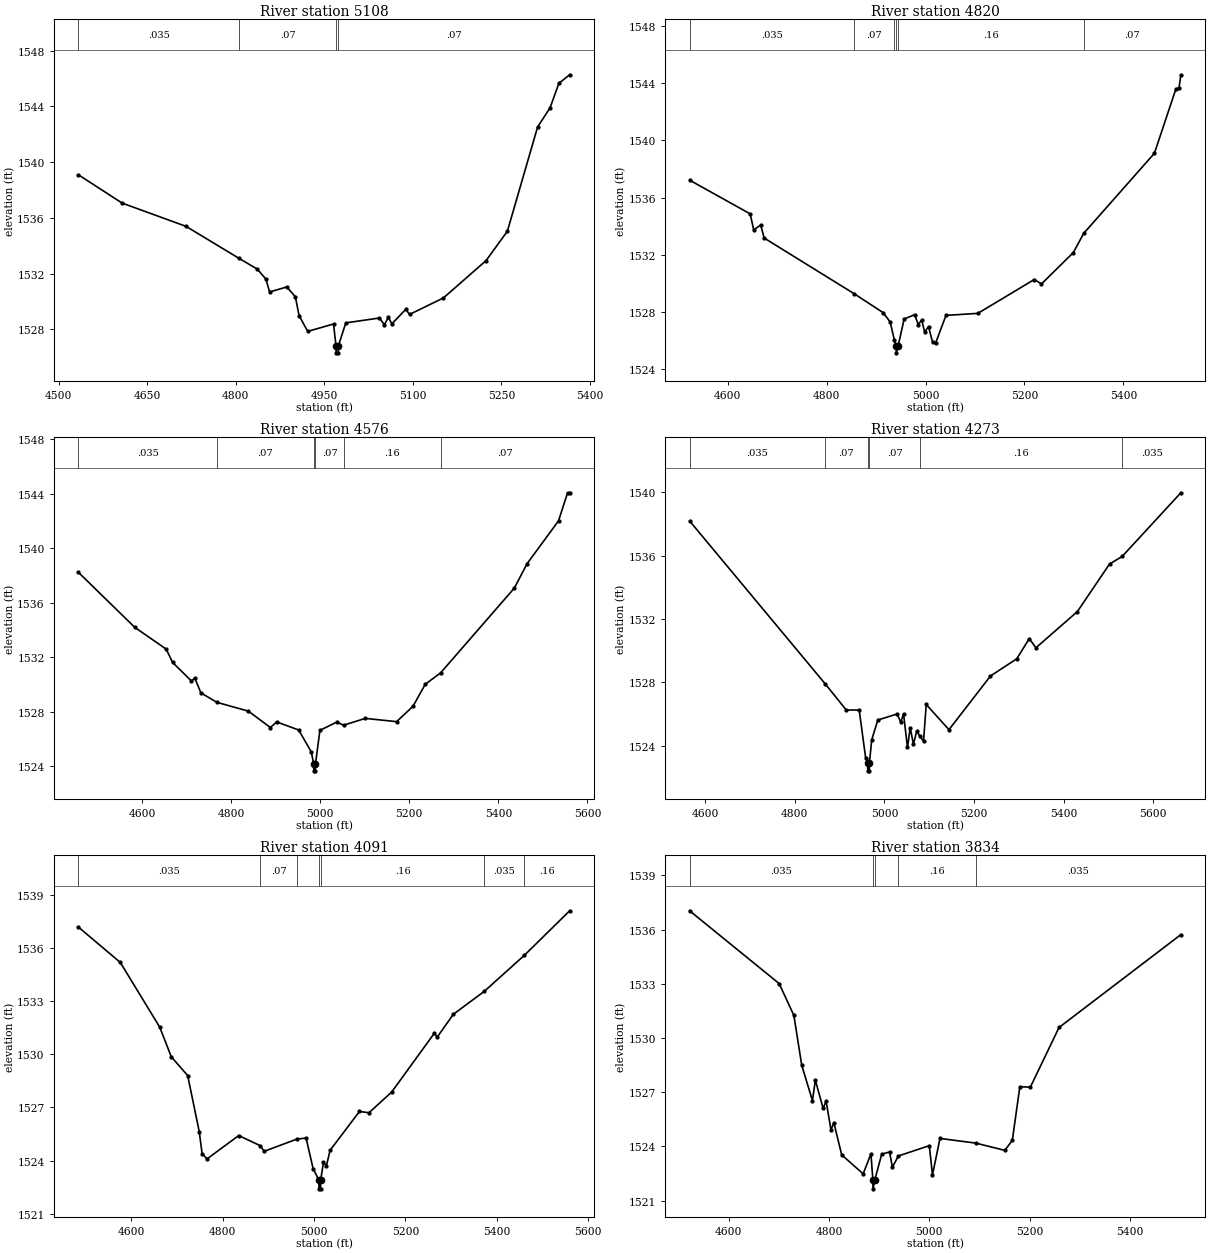
Type RM Length L Ch R = 1,5108,288,288,288
BEGIN DESCRIPTION:
Chimney Creek 1150 6.0
END DESCRIPTION:
XS GIS Cut Line= 3
      1629060.33      7006536.68      1628688.33      7006255.52
      1628383.26      7006054.05
#Sta/Elev= 30
  4533.7 1539.09  4607.7 1537.06  4715.9 1535.39  4805.8 1533.09  4836.6 1532.32
  4851.2 1531.60  4857.5 1530.68  4886.6 1531.04  4901.1 1530.33  4907.4 1528.98
  4922.0 1527.85  4965.7 1528.38  4969.9 1526.81  4970.2 1526.31  4973.7 1526.31
  4973.9 1526.81  4986.5 1528.46  5043.4 1528.81  5051.9 1528.32  5058.5 1528.87
  5064.5 1528.39  5087.9 1529.43  5094.6 1529.07  5151.8 1530.25  5224.0 1532.93
  5260.1 1535.04  5311.3 1542.52  5332.4 1543.90  5347.4 1545.66  5365.6 1546.27
#Mann=4,-1,0
  4533.7   0.035       0  4805.8    0.07       0  4969.9    0.07       0
  4973.9    0.07       0
Bank Sta=4969.9,4973.9
Exp/Cntr=0.3,0.1

Type RM Length L Ch R = 1,4820,244,244,244
BEGIN DESCRIPTION:
Mapping XS 8c0f5ba6
END DESCRIPTION:
XS GIS Cut Line= 3
      1629213.12      7006403.01      1628876.30      7006064.45
      1628469.18      7005749.16
#Sta/Elev= 30
  4523.4 1537.22  4645.8 1534.86  4652.9 1533.74  4667.0 1534.08  4674.1 1533.17
  4856.1 1529.27  4914.5 1527.95  4928.7 1527.29  4936.9 1526.06  4940.8 1525.64
  4941.0 1525.14  4944.8 1525.64  4956.9 1527.51  4978.2 1527.81  4985.2 1527.12
  4992.3 1527.43  4998.3 1526.59  5006.1 1526.98  5014.3 1525.87  5020.6 1525.84
  5041.4 1527.76  5105.7 1527.90  5219.8 1530.27  5234.3 1529.96  5298.6 1532.15
  5319.7 1533.50  5462.5 1539.10  5505.9 1543.60  5512.2 1543.66  5515.9 1544.59
#Mann=6,-1,0
  4523.4   0.035       0  4856.1    0.07       0  4936.9    0.16       0
  4940.8    0.07       0  4944.8    0.16       0  5319.7    0.07       0
Bank Sta=4940.8,4944.8
Exp/Cntr=0.3,0.1

Type RM Length L Ch R = 1,4576,303,303,303
BEGIN DESCRIPTION:
Mapping XS 1a75e83d
END DESCRIPTION:
XS GIS Cut Line= 3
      1629407.57      7006264.13      1629006.51      7005896.05
      1628570.77      7005547.11
#Sta/Elev= 30
  4457.4 1538.23  4583.6 1534.20  4654.5 1532.59  4668.7 1531.62  4711.2 1530.25
  4718.6 1530.47  4732.4 1529.38  4768.1 1528.69  4838.9 1528.04  4888.2 1526.84
  4902.4 1527.25  4951.7 1526.66  4980.1 1525.05  4985.5 1524.16  4985.7 1523.66
  4989.2 1523.66  4989.5 1524.16  4999.4 1526.63  5037.2 1527.24  5052.7 1527.01
  5101.2 1527.51  5171.6 1527.27  5208.4 1528.40  5235.7 1530.01  5270.3 1530.85
  5435.7 1537.07  5464.5 1538.87  5535.0 1542.01  5555.3 1544.07  5560.0 1544.07
#Mann=6,-1,0
  4457.4   0.035       0  4768.1    0.07       0  4985.5    0.07       0
  4989.5    0.07       0  5052.7    0.16       0  5270.3    0.07       0
Bank Sta=4985.5,4989.5
Exp/Cntr=0.3,0.1

Type RM Length L Ch R = 1,4273,182,182,182
BEGIN DESCRIPTION:
Mapping XS 04faddfb
END DESCRIPTION:
XS GIS Cut Line= 3
      1629537.73      7006116.51      1629265.19      7005772.79
      1628723.51      7005399.51
#Sta/Elev= 30
  4565.1 1538.19  4867.3 1527.92  4914.8 1526.25  4943.7 1526.25  4958.1 1523.21
  4962.5 1522.91  4962.8 1522.41  4966.3 1522.41  4966.5 1522.91  4971.6 1524.37
  4985.3 1525.62  5028.3 1526.00  5036.5 1525.48  5042.6 1526.01  5051.4 1523.89
  5057.5 1525.13  5064.7 1524.09  5072.3 1524.94  5078.6 1524.61  5087.2 1524.28
  5093.3 1526.60  5144.0 1525.01  5236.7 1528.40  5295.5 1529.49  5323.2 1530.76
  5338.1 1530.18  5430.7 1532.47  5502.4 1535.47  5530.6 1535.95  5661.6 1539.97
#Mann=6,-1,0
  4565.1   0.035       0  4867.3    0.07       0  4962.5    0.07       0
  4966.5    0.07       0  5078.6    0.16       0  5530.6   0.035       0
Bank Sta=4962.5,4966.5
Exp/Cntr=0.3,0.1

Type RM Length L Ch R = 1,4091,257,257,257
BEGIN DESCRIPTION:
Mapping XS 5564e3c6
END DESCRIPTION:
XS GIS Cut Line= 3
      1629789.45      7005783.19      1629303.38      7005606.12
      1628862.39      7005264.09
#Sta/Elev= 30
  4484.1 1537.19  4575.8 1535.19  4662.2 1531.53  4687.4 1529.86  4723.3 1528.80
  4748.6 1525.63  4754.9 1524.39  4765.6 1524.09  4835.0 1525.41  4882.1 1524.84
  4890.8 1524.52  4962.4 1525.21  4982.5 1525.27  4997.9 1523.54  5010.4 1522.90
  5010.7 1522.40  5014.2 1522.40  5014.4 1522.90  5020.6 1523.90  5026.9 1523.69
  5035.1 1524.58  5099.3 1526.77  5120.2 1526.70  5169.9 1527.87  5263.2 1531.19
  5269.5 1530.97  5304.8 1532.26  5372.7 1533.56  5460.6 1535.60  5559.5 1538.11
#Mann=7,-1,0
  4484.1   0.035       0  4882.1    0.07       0  4962.4    0.16       0
  5010.4    0.07       0  5014.4    0.16       0  5372.7   0.035       0
  5460.6    0.16       0
Bank Sta=5010.4,5014.4
Exp/Cntr=0.3,0.1

Type RM Length L Ch R = 1,3834,288,288,288
BEGIN DESCRIPTION:
Mapping XS 620c39e5
END DESCRIPTION:
XS GIS Cut Line= 3
      1629838.08      7005659.92      1629426.65      7005413.41
      1629011.68      7005135.61
#Sta/Elev= 30
  4522.3 1537.04  4700.8 1533.01  4730.1 1531.25  4745.7 1528.50  4767.1 1526.53
  4772.9 1527.67  4788.4 1526.10  4794.3 1526.51  4804.0 1524.92  4809.8 1525.31
  4825.4 1523.53  4868.2 1522.48  4883.7 1523.59  4887.5 1522.15  4887.8 1521.65
  4891.5 1522.15  4905.1 1523.57  4920.7 1523.69  4926.5 1522.85  4938.4 1523.47
  5000.0 1524.04  5006.3 1522.42  5021.3 1524.44  5092.9 1524.18  5150.4 1523.78
  5165.4 1524.33  5180.4 1527.30  5201.4 1527.28  5258.5 1530.58  5501.3 1535.72
#Mann=5,-1,0
  4522.3   0.035       0  4887.5    0.07       0  4891.5   0.035       0
  4938.4    0.16       0  5092.9   0.035       0
Bank Sta=4887.5,4891.5
Exp/Cntr=0.3,0.1

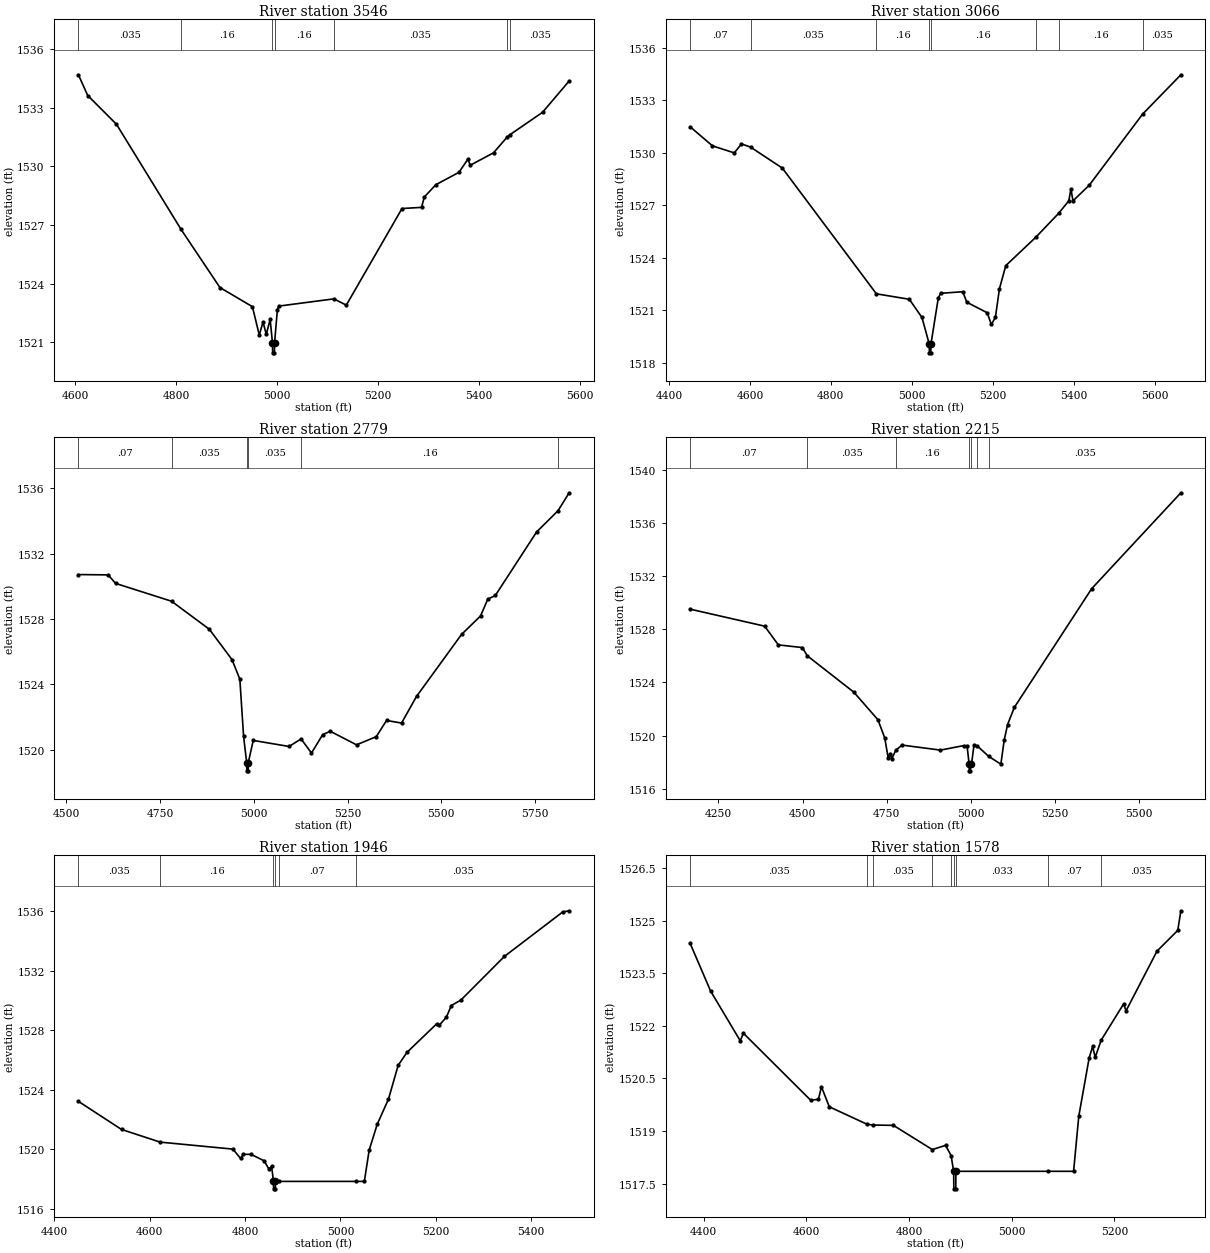
Type RM Length L Ch R = 1,3546,480,480,480
BEGIN DESCRIPTION:
Mapping XS 6e1fae42
END DESCRIPTION:
XS GIS Cut Line= 3
      1629912.73      7005486.30      1629615.88      7005222.44
      1629095.07      7004979.39
#Sta/Elev= 30
  4606.2 1534.69  4624.7 1533.63  4681.6 1532.16  4809.6 1526.78  4886.5 1523.81
  4950.9 1522.83  4964.4 1521.38  4971.8 1522.04  4978.4 1521.42  4986.0 1522.18
  4990.6 1520.97  4990.9 1520.47  4994.5 1520.47  4994.7 1520.97  5000.2 1522.65
  5002.9 1522.86  5112.1 1523.23  5136.8 1522.91  5247.1 1527.85  5285.8 1527.91
  5291.3 1528.44  5314.2 1529.07  5359.9 1529.70  5377.2 1530.36  5382.7 1530.07
  5428.4 1530.70  5454.9 1531.49  5461.2 1531.63  5525.4 1532.77  5578.1 1534.37
#Mann=7,-1,0
  4606.2   0.035       0  4809.6    0.16       0  4990.6    0.07       0
  4994.7    0.16       0  5112.1   0.035       0  5454.9    0.16       0
  5461.2   0.035       0
Bank Sta=4990.6,4994.7
Exp/Cntr=0.3,0.1

Type RM Length L Ch R = 1,3066,287,287,287
BEGIN DESCRIPTION:
Mapping XS acaf8a78
END DESCRIPTION:
XS GIS Cut Line= 3
      1630245.69      7005112.21      1629737.84      7004901.69
      1629080.25      7004819.22
#Sta/Elev= 30
  4452.3 1531.48  4507.5 1530.39  4561.3 1529.99  4579.2 1530.50  4601.6 1530.32
  4680.1 1529.12  4912.5 1521.94  4993.8 1521.63  5025.1 1520.59  5043.1 1519.07
  5043.4 1518.57  5047.0 1518.57  5047.3 1519.07  5065.4 1521.70  5071.2 1521.97
  5125.9 1522.06  5135.9 1521.46  5186.3 1520.86  5196.4 1520.19  5206.5 1520.59
  5216.6 1522.24  5232.2 1523.55  5306.3 1525.17  5362.5 1526.53  5387.9 1527.25
  5393.1 1527.93  5398.2 1527.25  5438.3 1528.14  5570.1 1532.20  5664.8 1534.45
#Mann=8,-1,0
  4452.3    0.07       0  4601.6   0.035       0  4912.5    0.16       0
  5043.1    0.07       0  5047.3    0.16       0  5306.3   0.035       0
  5362.5    0.16       0  5570.1   0.035       0
Bank Sta=5043.1,5047.3
Exp/Cntr=0.3,0.1

Type RM Length L Ch R = 1,2779,564,564,564
BEGIN DESCRIPTION:
Mapping XS e70c6dc8
END DESCRIPTION:
XS GIS Cut Line= 3
      1630351.98      7004617.41      1629894.09      7004734.59
      1629058.18      7004704.27
#Sta/Elev= 30
  4531.9 1530.72  4611.4 1530.70  4631.0 1530.18  4780.3 1529.09  4881.0 1527.38
  4941.7 1525.52  4962.6 1524.32  4972.6 1520.82  4980.8 1519.22  4981.1 1518.72
  4984.8 1518.72  4985.1 1519.22  4998.3 1520.58  5093.7 1520.21  5126.0 1520.67
  5153.7 1519.81  5183.8 1520.94  5203.8 1521.14  5273.8 1520.31  5326.6 1520.81
  5353.9 1521.80  5393.9 1521.64  5433.9 1523.27  5554.0 1527.06  5604.7 1528.19
  5624.0 1529.22  5644.1 1529.44  5754.1 1533.32  5811.6 1534.63  5841.0 1535.72
#Mann=6,-1,0
  4531.9    0.07       0  4780.3   0.035       0  4980.8   0.035       0
  4985.1   0.035       0  5126.0    0.16       0  5811.6   0.035       0
Bank Sta=4980.8,4985.1
Exp/Cntr=0.3,0.1

Type RM Length L Ch R = 1,2215,269,269,269
BEGIN DESCRIPTION:
Mapping XS 7d1756ed
END DESCRIPTION:
XS GIS Cut Line= 3
      1630422.02      7004494.14      1629604.31      7004324.00
      1628979.64      7004301.45
#Sta/Elev= 30
  4165.6 1529.52  4387.3 1528.24  4428.1 1526.83  4499.6 1526.63  4514.2 1526.01
  4652.8 1523.27  4724.3 1521.20  4744.8 1519.82  4755.0 1518.30  4760.2 1518.65
  4765.3 1518.24  4777.4 1518.89  4795.8 1519.29  4910.4 1518.91  4979.7 1519.25
  4989.9 1519.19  4995.8 1517.85  4996.1 1517.35  4999.8 1517.35  5000.1 1517.85
  5003.0 1517.85  5010.1 1519.27  5019.4 1519.24  5054.0 1518.44  5090.2 1517.85
  5100.2 1519.67  5110.2 1520.83  5130.2 1522.12  5360.4 1531.06  5625.9 1538.28
#Mann=7,-1,0
  4165.6    0.07       0  4514.2   0.035       0  4777.4    0.16       0
  4995.8    0.07       0  5000.1    0.16       0  5019.4    0.07       0
  5054.0   0.035       0
Bank Sta=4995.8,5000.1
Exp/Cntr=0.3,0.1

Type RM Length L Ch R = 1,1946,368,368,368
BEGIN DESCRIPTION:
Mapping XS 51c84e37
END DESCRIPTION:
XS GIS Cut Line= 3
      1629984.08      7004360.23      1629501.44      7004091.13
      1629030.91      7004165.79
#Sta/Elev= 30
  4450.5 1523.23  4541.0 1521.34  4622.0 1520.49  4774.6 1520.02  4790.6 1519.39
  4796.3 1519.67  4812.3 1519.67  4839.7 1519.24  4850.0 1518.68  4855.7 1518.87
  4859.5 1517.85  4859.8 1517.35  4863.5 1517.35  4863.8 1517.85  4870.7 1517.85
  5032.6 1517.85  5050.1 1517.85  5060.2 1519.95  5077.1 1521.69  5100.7 1523.38
  5121.0 1525.65  5139.4 1526.52  5201.7 1528.44  5206.7 1528.33  5222.2 1528.89
  5232.4 1529.67  5252.6 1530.04  5343.7 1532.97  5466.0 1535.96  5479.5 1536.04
#Mann=6,-1,0
  4450.5   0.035       0  4622.0    0.16       0  4859.5    0.07       0
  4863.8    0.16       0  4870.7    0.07       0  5032.6   0.035       0
Bank Sta=4859.5,4863.8
Exp/Cntr=0.3,0.1

Type RM Length L Ch R = 1,1578,139,139,139
BEGIN DESCRIPTION:
Mapping XS c25d63b2
END DESCRIPTION:
XS GIS Cut Line= 6
      1630043.03      7004353.88      1629803.44      7003970.18
      1629756.57      7003848.66      1629727.05      7003813.93
      1629652.40      7003761.85      1629418.97      7003801.62
#Sta/Elev= 30
  4373.6 1524.35  4413.5 1522.99  4471.3 1521.57  4477.2 1521.79  4608.2 1519.88
  4623.5 1519.90  4629.4 1520.26  4644.7 1519.69  4718.5 1519.19  4730.1 1519.17
  4769.6 1519.16  4845.4 1518.47  4871.2 1518.59  4881.9 1518.30  4887.0 1517.85
  4887.3 1517.35  4891.1 1517.35  4891.3 1517.85  5070.0 1517.85  5120.6 1517.85
  5130.7 1519.42  5151.0 1521.09  5157.7 1521.41  5162.7 1521.10  5174.3 1521.59
  5217.9 1522.62  5222.9 1522.43  5283.1 1524.13  5323.5 1524.72  5329.6 1525.28
#Mann=9,-1,0
  4373.6   0.035       0  4718.5    0.16       0  4730.1   0.035       0
  4845.4    0.07       0  4881.9   0.033       0  4887.0   0.033       0
  4891.3   0.033       0  5070.0    0.07       0  5174.3   0.035       0
Bank Sta=4887,4891.3
Exp/Cntr=0.3,0.1

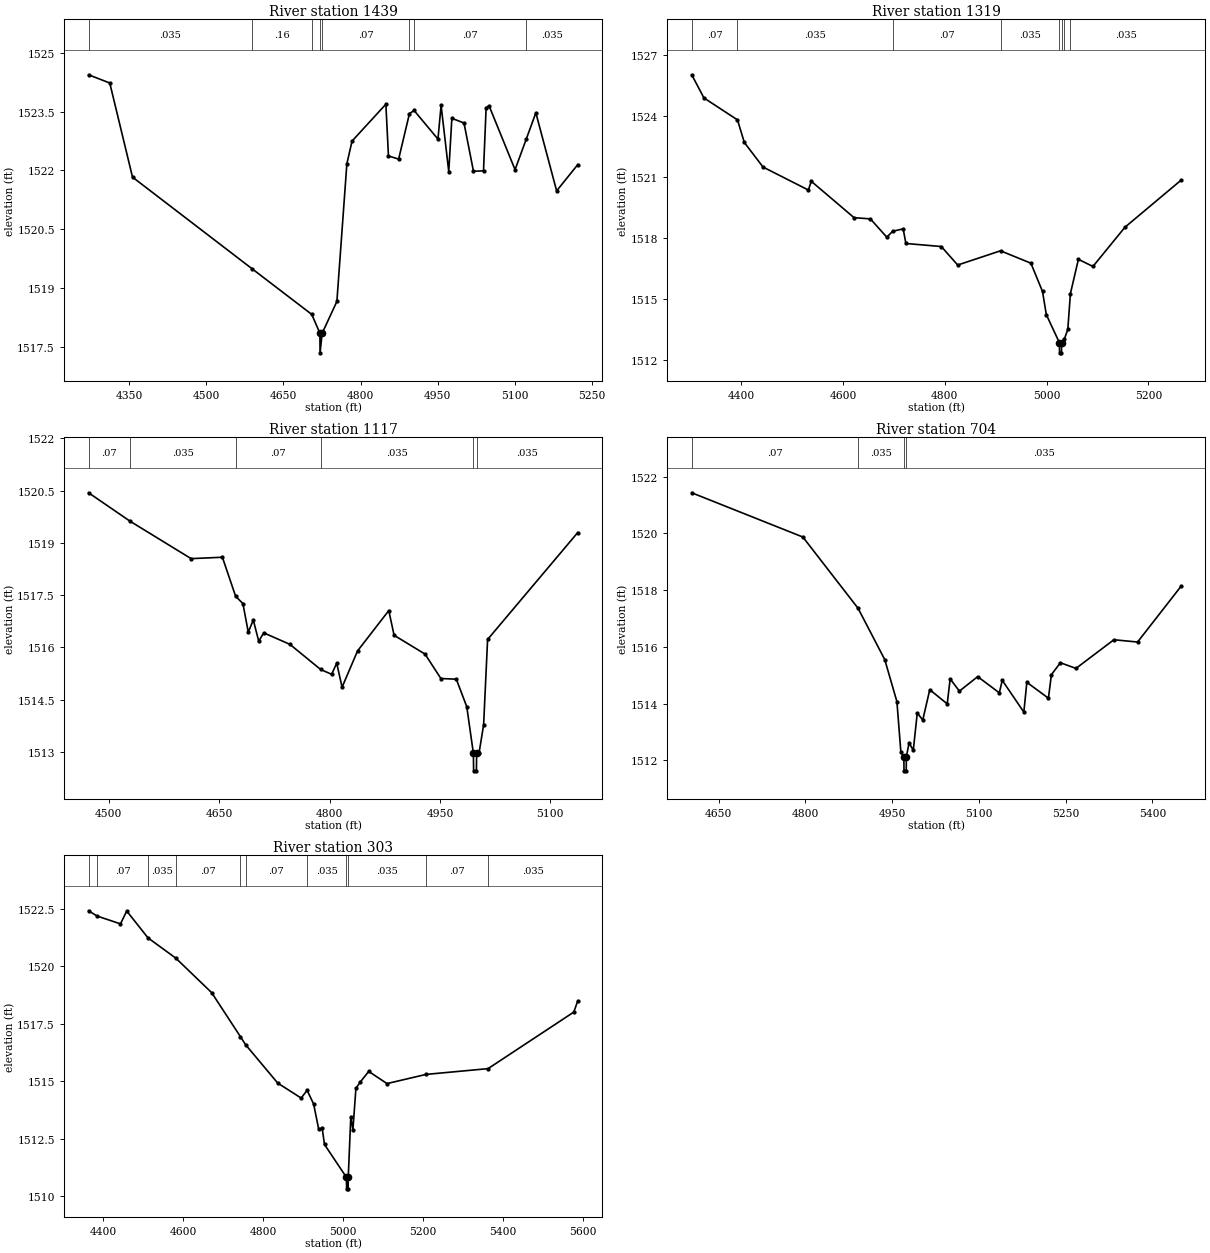
Type RM Length L Ch R = 1,1439,120,120,120
BEGIN DESCRIPTION:
Mapping XS 3547bb67
END DESCRIPTION:
XS GIS Cut Line= 6
      1630117.69      7004322.64      1629987.47      7004121.22
      1629883.30      7003945.88      1629862.47      7003744.49
      1629796.50      7003699.35      1629574.28      7003668.10
#Sta/Elev= 30
  4271.4 1524.44  4312.6 1524.23  4356.8 1521.83  4589.5 1519.49  4705.1 1518.33
  4720.9 1517.85  4721.2 1517.35  4725.3 1517.85  4753.9 1518.66  4773.3 1522.17
  4783.4 1522.75  4849.1 1523.69  4854.1 1522.37  4873.9 1522.29  4894.9 1523.45
  4903.9 1523.53  4950.3 1522.80  4956.4 1523.66  4971.3 1521.97  4977.3 1523.33
  5000.9 1523.21  5019.3 1521.98  5038.8 1521.99  5043.9 1523.60  5049.6 1523.65
  5100.1 1522.02  5121.6 1522.79  5140.5 1523.47  5180.9 1521.48  5222.0 1522.15
#Mann=8,-1,0
  4271.4   0.035       0  4589.5    0.16       0  4705.1    0.07       0
  4720.9    0.07       0  4725.3    0.07       0  4894.9   0.033       0
  4903.9    0.07       0  5121.6   0.035       0
Bank Sta=4720.9,4725.3
Exp/Cntr=0.3,0.1

Type RM Length L Ch R = 1,1319,202,202,202
BEGIN DESCRIPTION:
Mapping XS d9954198
END DESCRIPTION:
XS GIS Cut Line= 6
      1630211.41      7004305.22      1630058.65      7004055.25
      1629980.52      7003810.46      1629909.34      7003678.52
      1629827.75      7003609.07      1629678.33      7003571.29
#Sta/Elev= 30
  4302.8 1526.03  4326.8 1524.89  4392.7 1523.81  4406.1 1522.70  4442.9 1521.49
  4531.9 1520.36  4537.7 1520.79  4621.7 1519.00  4653.8 1518.94  4686.0 1518.04
  4697.5 1518.33  4718.2 1518.45  4723.5 1517.73  4793.1 1517.58  4825.3 1516.67
  4909.4 1517.37  4969.1 1516.76  4991.9 1515.37  4999.4 1514.23  5025.1 1512.85
  5025.4 1512.35  5029.2 1512.35  5029.5 1512.85  5035.0 1513.04  5041.6 1513.50
  5046.7 1515.26  5062.4 1516.95  5091.0 1516.60  5153.9 1518.53  5263.9 1520.84
#Mann=8,-1,0
  4302.8    0.07       0  4392.7   0.035       0  4697.5    0.07       0
  4909.4   0.035       0  5025.1   0.035       0  5029.5   0.035       0
  5035.0    0.07       0  5046.7   0.035       0
Bank Sta=5025.1,5029.5
Exp/Cntr=0.3,0.1

Type RM Length L Ch R = 1,1117,413,413,413
BEGIN DESCRIPTION:
Mapping XS d7f5ee42
END DESCRIPTION:
XS GIS Cut Line= 3
      1630318.74      7003881.09      1629959.34      7003497.38
      1629828.66      7003449.24
#Sta/Elev= 30
  4472.4 1520.44  4529.1 1519.62  4611.8 1518.55  4654.3 1518.59  4672.3 1517.47
  4682.2 1517.26  4689.5 1516.44  4696.3 1516.79  4703.7 1516.18  4710.5 1516.42
  4746.1 1516.09  4787.8 1515.37  4802.8 1515.23  4809.7 1515.55  4817.0 1514.86
  4838.0 1515.90  4880.5 1517.06  4887.7 1516.35  4929.8 1515.81  4951.3 1515.11
  4972.3 1515.09  4986.5 1514.30  4995.5 1512.96  4995.8 1512.46  4999.6 1512.46
  4999.9 1512.96  5003.1 1512.96  5009.4 1513.78  5014.8 1516.23  5137.4 1519.30
#Mann=6,-1,0
  4472.4    0.07       0  4529.1   0.035       0  4672.3    0.07       0
  4787.8   0.035       0  4995.5   0.035       0  4999.9   0.035       0
Bank Sta=4995.5,4999.9
Exp/Cntr=0.3,0.1

Type RM Length L Ch R = 1,704,401,401,401
BEGIN DESCRIPTION:
Mapping XS 5d5db84b
END DESCRIPTION:
XS GIS Cut Line= 3
      1630627.72      7003776.87      1630339.55      7003504.33
      1629902.02      7003401.89
#Sta/Elev= 30
  4603.3 1521.43  4795.5 1519.87  4890.9 1517.36  4937.1 1515.55  4958.1 1514.07
  4965.0 1512.28  4970.1 1512.13  4970.4 1511.63  4974.2 1511.63  4974.5 1512.13
  4979.2 1512.62  4986.4 1512.35  4993.3 1513.67  5002.8 1513.42  5014.9 1514.49
  5045.1 1513.99  5050.2 1514.87  5066.2 1514.44  5097.8 1514.95  5135.2 1514.38
  5140.3 1514.82  5177.6 1513.70  5182.8 1514.75  5220.1 1514.19  5225.3 1515.02
  5240.8 1515.44  5267.7 1515.24  5333.3 1516.25  5374.3 1516.17  5449.3 1518.13
#Mann=4,-1,0
  4603.3    0.07       0  4890.9   0.035       0  4970.1   0.035       0
  4974.5   0.035       0
Bank Sta=4970.1,4974.5
Exp/Cntr=0.3,0.1

Type RM Length L Ch R = 1,303,0,0,0
BEGIN DESCRIPTION:
Chimney Creek 1150 1.0
END DESCRIPTION:
XS GIS Cut Line= 3
      1630780.02      7003713.04      1630454.71      7003165.14
      1629905.51      7003372.39
#Sta/Elev= 30
  4362.8 1522.41  4384.2 1522.18  4442.7 1521.84  4458.3 1522.40  4511.6 1521.23
  4581.0 1520.35  4670.7 1518.85  4742.9 1516.93  4755.8 1516.58  4836.3 1514.91
  4894.8 1514.26  4909.7 1514.60  4926.0 1514.00  4938.5 1512.92  4947.4 1512.94
  4953.2 1512.24  5008.1 1510.81  5008.5 1510.31  5012.3 1510.31  5012.6 1510.81
  5019.0 1513.45  5024.3 1512.88  5031.8 1514.68  5042.4 1514.95  5063.8 1515.42
  5109.6 1514.89  5207.4 1515.29  5362.4 1515.54  5576.9 1518.00  5587.0 1518.49
#Mann=11,-1,0
  4362.8   0.035       0  4384.2    0.07       0  4511.6   0.035       0
  4581.0    0.07       0  4742.9   0.035       0  4755.8    0.07       0
  4909.7   0.035       0  5008.1   0.035       0  5012.6   0.035       0
  5207.4    0.07       0  5362.4   0.035       0
Bank Sta=5008.1,5012.6
Exp/Cntr=0.3,0.1

Chan Stop Cuts=-1