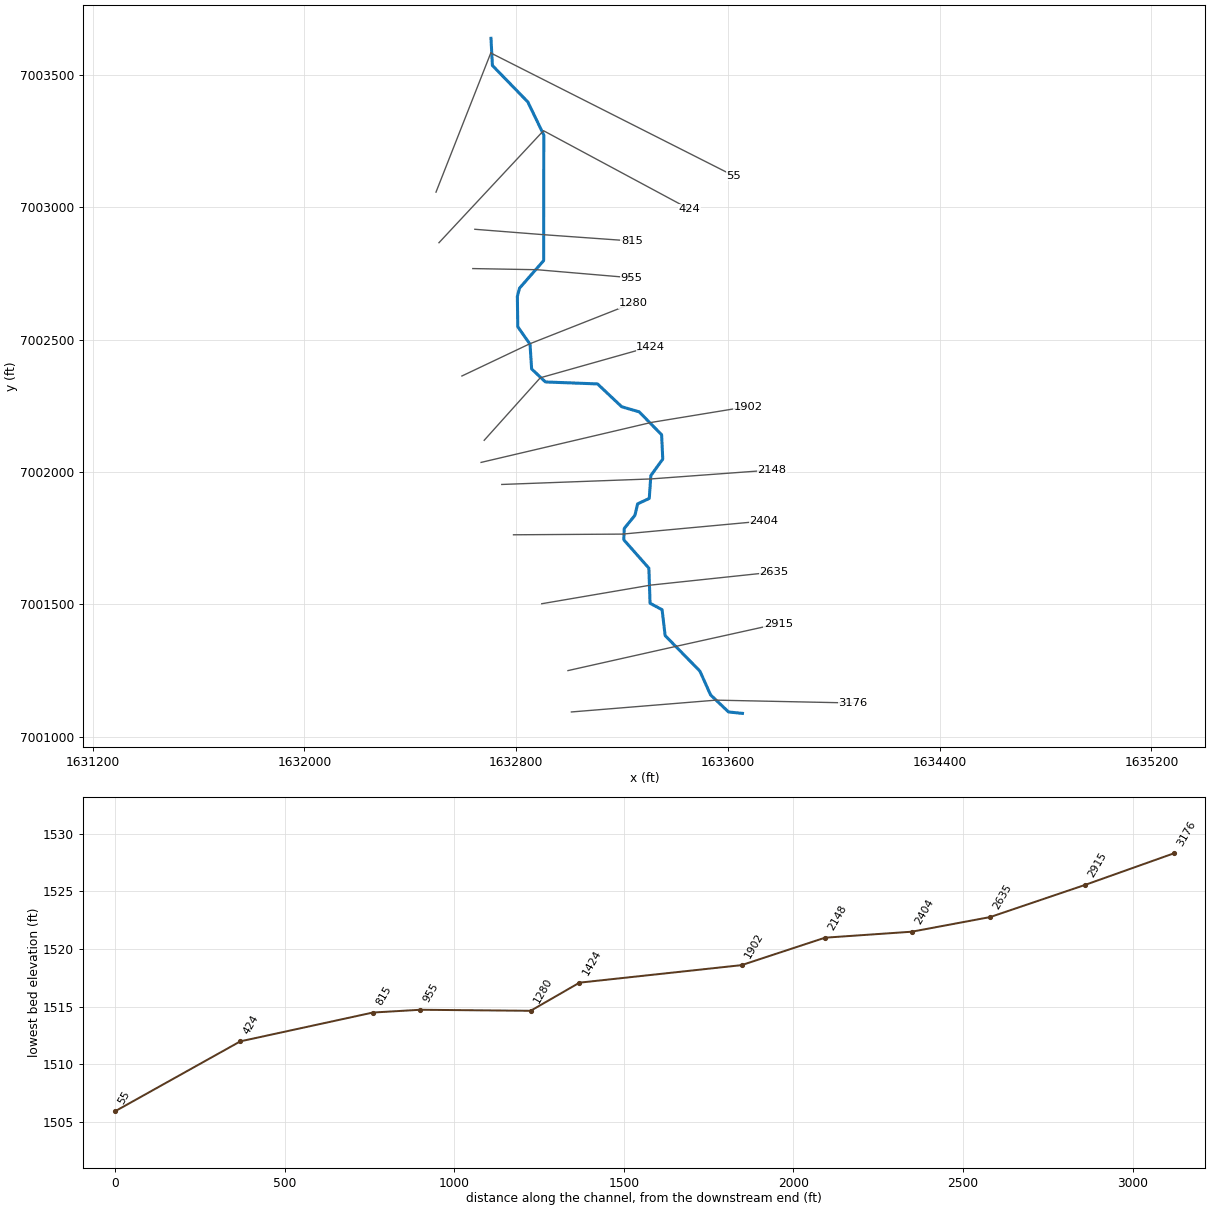
--- Chimney Creek 1151.prj (project) ---

Proj Title=Chimney Creek 1151 Base Level Engineering
Current Plan=p01
Default Exp/Contr=0.3,0.1
English Units
Geom File=g01
Flow File=f01
Plan File=p01
BEGIN DESCRIPTION:
Chimney Creek 1151
END DESCRIPTION:

--- Chimney Creek 1151.p01 (plan) ---

Plan Title=Multiple Run
Short Identifier=Multiple
Geom File=g01
Flow File=f01
Subcritical Flow
K Sum by GR= 0
Std Step Tol= 0.01
Critical Tol= 0.01
Num of Std Step Trials= 20
Max Error Tol= 0.3
Flow Tol Ratio= 0.001
Split Flow NTrial= 30
Split Flow Tol= 0.02
Split Flow Ratio= 0.02
Log Output Level= 0
Friction Slope Method= 1
Unsteady Friction Slope Method= 2
Unsteady Bridges Friction Slope Method= 1
Parabolic Critical Depth
Global Vel Dist=  1 , 1 , 1
Global Log Level= 0
CheckData=True
Encroach Param= -1, 0, 0, 0
BEGIN DESCRIPTION:
Multiple Run
END DESCRIPTION:

--- Chimney Creek 1151.f01 (steady flow) ---

Flow Title=Multiple
Number of Profiles=7
Profile Names=10-year,25-year,50-year,1pct_min,100-year,1pct_plu,500-year
River Rch & RM= Chimney Creek 11,Reach-1,3176
     174     232     278     166     331     660     474
River Rch & RM= Chimney Creek 11,Reach-1,2635
     198     266     321     193     385     768     560
Boundary for River Rch & Prof#=Chimney Creek 11,Reach-1,1
Up Type=0
Dn Type=3
Dn Slope=0.005
Boundary for River Rch & Prof#=Chimney Creek 11,Reach-1,2
Up Type=0
Dn Type=3
Dn Slope=0.005
Boundary for River Rch & Prof#=Chimney Creek 11,Reach-1,3
Up Type=0
Dn Type=3
Dn Slope=0.005
Boundary for River Rch & Prof#=Chimney Creek 11,Reach-1,4
Up Type=0
Dn Type=3
Dn Slope=0.005
Boundary for River Rch & Prof#=Chimney Creek 11,Reach-1,5
Up Type=0
Dn Type=3
Dn Slope=0.005
Boundary for River Rch & Prof#=Chimney Creek 11,Reach-1,6
Up Type=0
Dn Type=3
Dn Slope=0.005
Boundary for River Rch & Prof#=Chimney Creek 11,Reach-1,7
Up Type=0
Dn Type=3
Dn Slope=0.005

--- Chimney Creek 1151.g01 (geometry) ---

Geom Title=Existing Conditions

River Reach=Chimney Creek 11,Reach-1
Reach XY= 30
      1633655.00      7001088.00      1633602.46      7001093.30
      1633534.57      7001157.78      1633494.22      7001247.68
      1633362.88      7001381.87      1633351.44      7001479.50
      1633305.97      7001503.96      1633301.44      7001636.52
      1633206.74      7001743.63      1633208.30      7001786.29
      1633248.74      7001836.12      1633258.89      7001879.36
      1633302.97      7001899.99      1633308.88      7001986.33
      1633353.90      7002048.55      1633349.61      7002140.44
      1633264.70      7002227.23      1633198.96      7002246.18
      1633107.45      7002332.53      1632910.65      7002339.97
      1632858.51      7002389.25      1632852.52      7002482.43
      1632806.20      7002548.51      1632804.68      7002663.11
      1632812.82      7002694.18      1632903.94      7002798.44
      1632904.49      7003272.79      1632844.24      7003397.68
      1632710.35      7003535.50      1632705.00      7003638.00

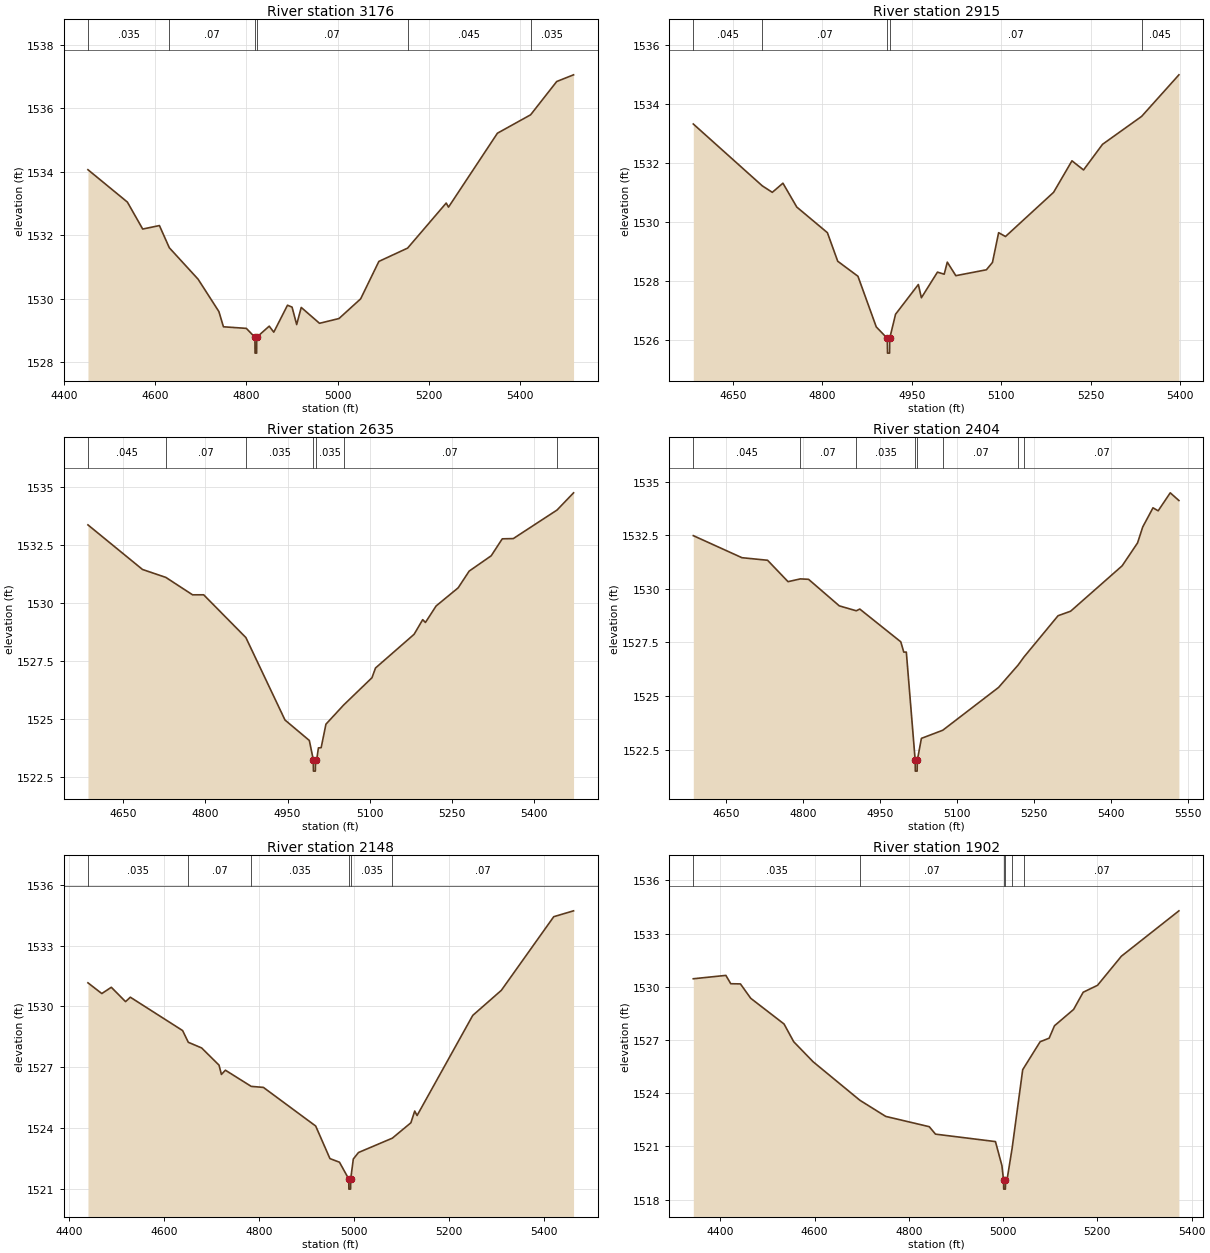
Type RM Length L Ch R = 1,3176,261,261,261
BEGIN DESCRIPTION:
Chimney Creek 1151 5.0
END DESCRIPTION:
XS GIS Cut Line= 3
      1633008.75      7001093.35      1633555.00      7001138.00
      1634071.92      7001127.24
#Sta/Elev= 30
  4452.5 1534.06  4539.0 1533.04  4572.6 1532.19  4609.3 1532.30  4631.0 1531.60
  4694.1 1530.61  4739.7 1529.59  4749.7 1529.11  4799.9 1529.06  4818.7 1528.78
  4819.0 1528.28  4822.5 1528.28  4822.7 1528.78  4850.1 1529.13  4860.1 1528.94
  4890.2 1529.79  4900.2 1529.73  4910.3 1529.18  4920.3 1529.72  4960.4 1529.22
  5003.1 1529.37  5050.6 1529.99  5090.6 1531.17  5153.7 1531.59  5238.3 1533.01
  5243.3 1532.88  5350.6 1535.21  5423.4 1535.79  5480.7 1536.84  5517.6 1537.05
#Mann=6,-1,0
  4452.5   0.035       0  4631.0    0.07       0  4818.7    0.07       0
  4822.7    0.07       0  5153.7   0.045       0  5423.4   0.035       0
Bank Sta=4818.7,4822.7
Exp/Cntr=0.3,0.1

Type RM Length L Ch R = 1,2915,280,280,280
BEGIN DESCRIPTION:
Mapping XS 3214db38
END DESCRIPTION:
XS GIS Cut Line= 3
      1632995.79      7001249.60      1633402.03      7001340.74
      1633789.99      7001426.67
#Sta/Elev= 30
  4583.8 1533.33  4699.4 1531.23  4716.2 1531.01  4734.0 1531.32  4757.2 1530.51
  4808.5 1529.64  4825.8 1528.67  4859.7 1528.16  4890.4 1526.44  4908.9 1526.05
  4909.2 1525.55  4912.7 1525.55  4912.9 1526.05  4922.7 1526.87  4960.9 1527.88
  4966.0 1527.43  4992.9 1528.30  5004.2 1528.23  5009.4 1528.64  5023.7 1528.18
  5074.9 1528.38  5085.1 1528.63  5095.4 1529.64  5106.9 1529.51  5187.5 1531.01
  5218.3 1532.08  5237.7 1531.77  5269.5 1532.64  5335.1 1533.59  5397.5 1535.00
#Mann=5,-1,0
  4583.8   0.045       0  4699.4    0.07       0  4908.9    0.07       0
  4912.9    0.07       0  5335.1   0.045       0
Bank Sta=4908.9,4912.9
Exp/Cntr=0.3,0.1

Type RM Length L Ch R = 1,2635,231,231,231
BEGIN DESCRIPTION:
Mapping XS 2ff4fc41
END DESCRIPTION:
XS GIS Cut Line= 3
      1632896.79      7001502.20      1633308.28      7001572.52
      1633774.41      7001621.99
#Sta/Elev= 30
  4585.8 1533.36  4685.4 1531.44  4727.9 1531.10  4776.7 1530.35  4797.0 1530.35
  4874.0 1528.51  4945.4 1524.96  4989.8 1524.08  4997.0 1523.26  4997.3 1522.76
  5000.8 1522.76  5001.1 1523.26  5003.3 1523.26  5006.4 1523.76  5011.4 1523.77
  5020.1 1524.78  5052.2 1525.60  5104.1 1526.78  5110.6 1527.20  5181.0 1528.65
  5196.7 1529.28  5201.7 1529.16  5221.2 1529.87  5261.4 1530.65  5281.5 1531.37
  5321.7 1532.03  5341.9 1532.76  5362.0 1532.77  5441.9 1534.00  5472.0 1534.74
#Mann=7,-1,0
  4585.8   0.045       0  4727.9    0.07       0  4874.0   0.035       0
  4997.0   0.035       0  5001.1   0.035       0  5052.2    0.07       0
  5441.9   0.045       0
Bank Sta=4997,5001.1
Exp/Cntr=0.3,0.1

Type RM Length L Ch R = 1,2404,256,256,256
BEGIN DESCRIPTION:
Mapping XS 111996d0
END DESCRIPTION:
XS GIS Cut Line= 3
      1632790.06      7001762.62      1633201.51      7001765.22
      1633735.37      7001814.70
#Sta/Elev= 30
  4585.5 1532.49  4680.4 1531.46  4730.4 1531.34  4770.4 1530.34  4794.4 1530.47
  4810.4 1530.45  4870.4 1529.21  4903.5 1528.98  4910.4 1529.06  4990.4 1527.53
  4996.2 1527.05  5001.2 1527.05  5018.5 1521.99  5018.7 1521.49  5022.3 1521.49
  5022.6 1521.99  5030.6 1523.02  5072.3 1523.40  5181.2 1525.40  5219.5 1526.45
  5230.7 1526.82  5297.3 1528.75  5321.8 1528.96  5422.3 1531.08  5452.4 1532.15
  5462.4 1532.89  5482.5 1533.79  5492.6 1533.65  5516.2 1534.49  5533.1 1534.13
#Mann=8,-1,0
  4585.5   0.045       0  4794.4    0.07       0  4903.5   0.035       0
  5018.5   0.035       0  5022.6   0.035       0  5072.3    0.07       0
  5219.5   0.035       0  5230.7    0.07       0
Bank Sta=5018.5,5022.6
Exp/Cntr=0.3,0.1

Type RM Length L Ch R = 1,2148,246,246,246
BEGIN DESCRIPTION:
Mapping XS f0be87d4
END DESCRIPTION:
XS GIS Cut Line= 3
      1632745.81      7001952.73      1633308.28      7001973.56
      1633766.58      7002007.41
#Sta/Elev= 30
  4439.6 1531.17  4468.8 1530.64  4488.8 1530.95  4518.8 1530.24  4528.8 1530.46
  4638.9 1528.81  4650.9 1528.23  4679.0 1527.95  4715.6 1527.10  4720.6 1526.64
  4729.0 1526.85  4783.4 1526.05  4809.0 1526.00  4919.1 1524.09  4949.1 1522.48
  4969.2 1522.30  4988.7 1521.47  4989.0 1520.97  4992.6 1520.97  4992.8 1521.47
  4998.3 1522.46  5009.2 1522.78  5080.5 1523.49  5119.5 1524.25  5127.6 1524.83
  5132.6 1524.61  5249.8 1529.56  5310.0 1530.80  5420.3 1534.44  5462.0 1534.73
#Mann=6,-1,0
  4439.6   0.035       0  4650.9    0.07       0  4783.4   0.035       0
  4988.7   0.035       0  4992.8   0.035       0  5080.5    0.07       0
Bank Sta=4988.7,4992.8
Exp/Cntr=0.3,0.1

Type RM Length L Ch R = 1,1902,478,478,478
BEGIN DESCRIPTION:
Mapping XS a607c0f2
END DESCRIPTION:
XS GIS Cut Line= 3
      1632667.64      7002036.05      1633310.88      7002187.10
      1633675.46      7002246.99
#Sta/Elev= 30
  4342.8 1530.45  4411.9 1530.64  4422.3 1530.17  4442.8 1530.16  4464.6 1529.35
  4535.3 1527.90  4555.8 1526.90  4597.0 1525.77  4696.2 1523.60  4751.0 1522.69
  4843.4 1522.11  4856.6 1521.69  4983.8 1521.27  4997.5 1519.92  5001.0 1519.09
  5001.3 1518.59  5004.9 1518.59  5005.1 1519.09  5008.2 1519.09  5019.1 1520.88
  5041.6 1525.32  5044.1 1525.43  5078.6 1526.90  5097.7 1527.10  5109.0 1527.80
  5149.6 1528.72  5169.9 1529.69  5200.3 1530.08  5250.9 1531.72  5373.0 1534.28
#Mann=6,-1,0
  4342.8   0.035       0  4696.2    0.07       0  5001.0    0.07       0
  5005.1    0.07       0  5019.1   0.035       0  5044.1    0.07       0
Bank Sta=5001,5005.1
Exp/Cntr=0.3,0.1

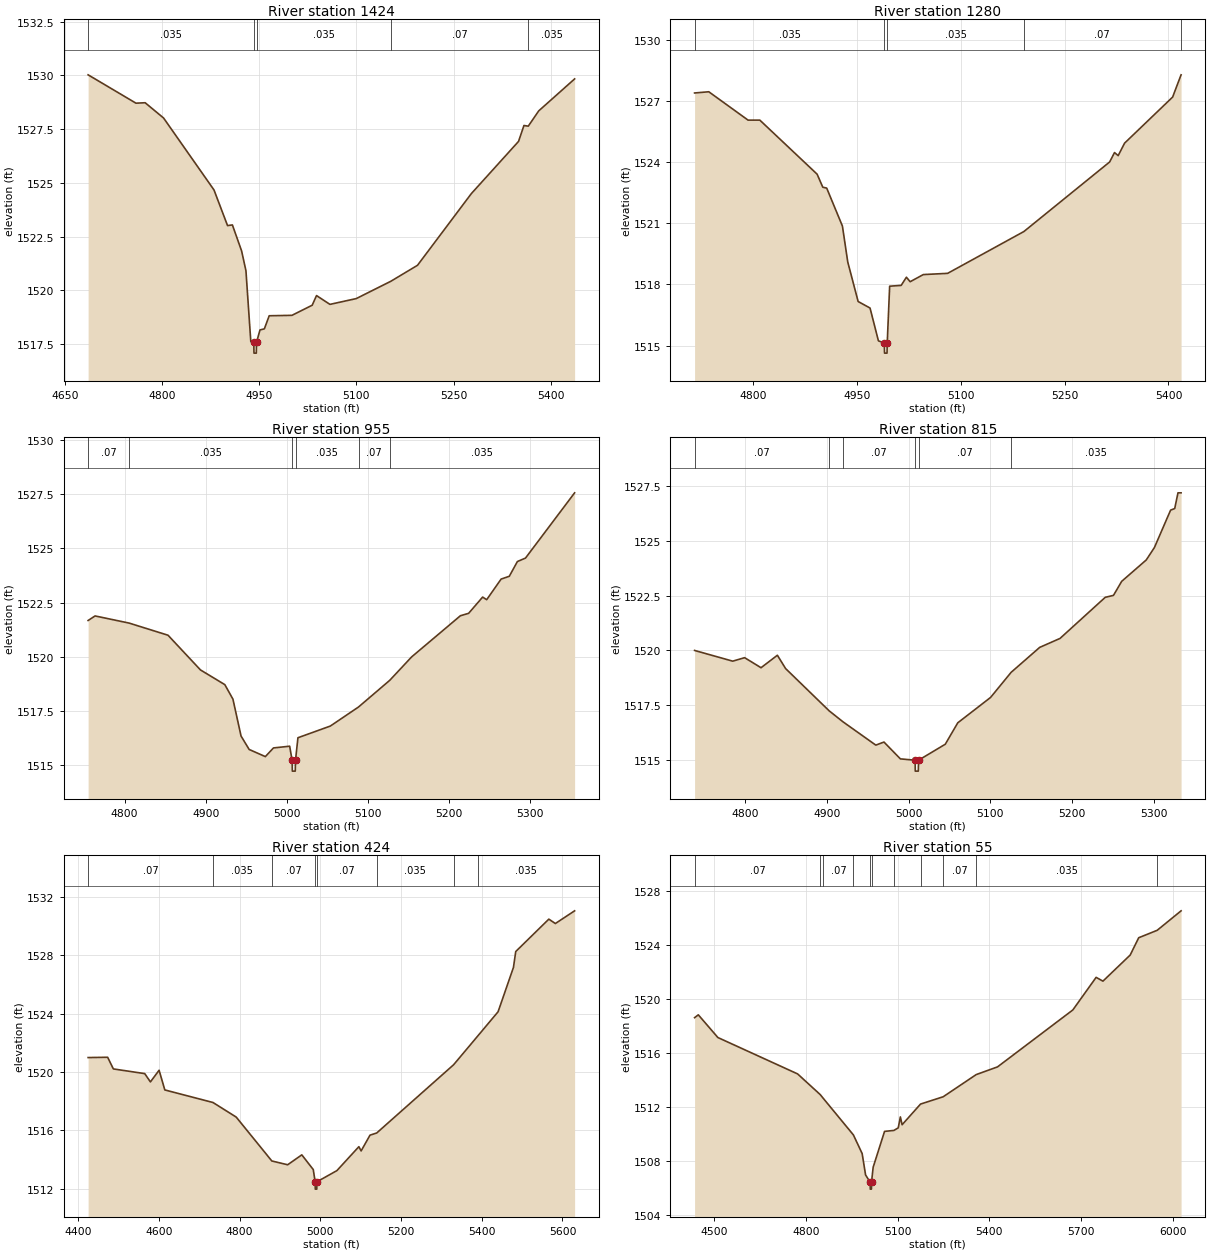
Type RM Length L Ch R = 1,1424,144,144,144
BEGIN DESCRIPTION:
Mapping XS d10d0217
END DESCRIPTION:
XS GIS Cut Line= 3
      1632679.35      7002119.55      1632891.18      7002355.68
      1633308.27      7002473.37
#Sta/Elev= 30
  4686.1 1530.03  4759.9 1528.71  4774.1 1528.73  4802.5 1528.02  4880.3 1524.67
  4901.2 1523.01  4908.7 1523.04  4922.9 1521.83  4929.6 1520.91  4937.1 1517.61
  4941.7 1517.57  4942.0 1517.07  4945.6 1517.07  4945.9 1517.57  4951.3 1518.15
  4958.0 1518.20  4965.5 1518.81  5000.6 1518.83  5031.8 1519.30  5038.5 1519.75
  5059.2 1519.34  5099.8 1519.61  5153.4 1520.42  5194.3 1521.16  5277.4 1524.50
  5350.2 1526.93  5358.5 1527.67  5365.2 1527.64  5381.3 1528.35  5436.7 1529.84
#Mann=5,-1,0
  4686.1   0.035       0  4941.7   0.035       0  4945.9   0.035       0
  5153.4    0.07       0  5365.2   0.035       0
Bank Sta=4941.7,4945.9
Exp/Cntr=0.3,0.1

Type RM Length L Ch R = 1,1280,325,325,325
BEGIN DESCRIPTION:
Mapping XS eab5ab12
END DESCRIPTION:
XS GIS Cut Line= 3
      1632595.21      7002362.47      1632851.25      7002483.97
      1633240.93      7002637.68
#Sta/Elev= 30
  4715.9 1527.38  4736.4 1527.44  4793.1 1526.05  4810.1 1526.05  4892.8 1523.40
  4901.0 1522.76  4906.6 1522.72  4929.3 1520.86  4937.0 1519.10  4952.0 1517.16
  4969.2 1516.84  4981.3 1515.23  4989.8 1515.13  4990.1 1514.63  4993.7 1514.63
  4994.0 1515.13  4997.5 1517.91  5014.1 1517.95  5021.7 1518.35  5027.1 1518.13
  5046.1 1518.48  5081.2 1518.54  5191.3 1520.59  5315.1 1524.00  5322.1 1524.46
  5327.4 1524.31  5336.6 1524.92  5406.0 1527.18  5417.5 1528.21  5418.2 1528.27
#Mann=5,-1,0
  4715.9   0.035       0  4989.8   0.035       0  4994.0   0.035       0
  5191.3    0.07       0  5417.5   0.035       0
Bank Sta=4989.8,4994
Exp/Cntr=0.3,0.1

Type RM Length L Ch R = 1,955,140,140,140
BEGIN DESCRIPTION:
Mapping XS c0335a67
END DESCRIPTION:
XS GIS Cut Line= 3
      1632636.38      7002768.26      1632879.46      7002763.92
      1633235.34      7002733.54
#Sta/Elev= 30
  4755.0 1521.67  4763.6 1521.88  4805.6 1521.55  4853.6 1520.99  4893.6 1519.39
  4923.7 1518.71  4933.7 1518.04  4943.7 1516.34  4953.7 1515.72  4973.7 1515.39
  4983.7 1515.79  5003.7 1515.87  5006.7 1515.22  5007.0 1514.72  5010.6 1514.72
  5010.9 1515.22  5013.9 1516.26  5053.9 1516.80  5088.7 1517.68  5127.2 1518.91
  5154.2 1519.99  5214.4 1521.89  5224.5 1522.00  5241.8 1522.75  5246.8 1522.63
  5264.6 1523.58  5274.7 1523.71  5284.7 1524.39  5294.7 1524.55  5355.3 1527.56
#Mann=6,-1,0
  4755.0    0.07       0  4805.6   0.035       0  5006.7   0.035       0
  5010.9   0.035       0  5088.7    0.07       0  5127.2   0.035       0
Bank Sta=5006.7,5010.9
Exp/Cntr=0.3,0.1

Type RM Length L Ch R = 1,815,391,391,391
BEGIN DESCRIPTION:
Mapping XS 5b7d329c
END DESCRIPTION:
XS GIS Cut Line= 3
      1632643.98      7002916.71      1632903.33      7002896.30
      1633237.52      7002872.43
#Sta/Elev= 30
  4738.1 1520.00  4784.8 1519.51  4799.3 1519.67  4819.4 1519.21  4839.4 1519.78
  4849.5 1519.17  4902.7 1517.24  4919.5 1516.74  4959.8 1515.67  4969.8 1515.81
  4989.9 1515.04  5007.9 1514.98  5008.1 1514.48  5011.8 1514.48  5012.1 1514.98
  5044.8 1515.71  5060.1 1516.69  5100.2 1517.85  5125.4 1519.00  5160.3 1520.14
  5185.2 1520.55  5240.5 1522.43  5250.6 1522.52  5260.6 1523.16  5290.7 1524.14
  5300.7 1524.71  5320.5 1526.42  5325.5 1526.49  5329.5 1527.21  5333.3 1527.21
#Mann=6,-1,0
  4738.1    0.07       0  4902.7   0.035       0  4919.5    0.07       0
  5007.9    0.07       0  5012.1    0.07       0  5125.4   0.035       0
Bank Sta=5007.9,5012.1
Exp/Cntr=0.3,0.1

Type RM Length L Ch R = 1,424,369,369,369
BEGIN DESCRIPTION:
Mapping XS ef1d3e69
END DESCRIPTION:
XS GIS Cut Line= 3
      1632508.53      7002865.91      1632903.33      7003289.10
      1633455.62      7002992.38
#Sta/Elev= 30
  4424.5 1521.00  4472.9 1521.02  4487.1 1520.22  4564.8 1519.90  4578.9 1519.33
  4600.4 1520.13  4614.6 1518.78  4733.9 1517.92  4791.5 1516.92  4879.8 1513.91
  4919.0 1513.65  4954.1 1514.33  4982.5 1513.32  4987.2 1512.48  4987.5 1511.98
  4991.2 1511.98  4991.4 1512.48  5041.1 1513.25  5095.5 1514.89  5101.1 1514.60
  5123.1 1515.68  5139.8 1515.83  5330.4 1520.51  5389.9 1522.47  5440.5 1524.14
  5478.6 1527.18  5484.3 1528.27  5566.3 1530.49  5582.5 1530.19  5630.2 1531.06
#Mann=8,-1,0
  4424.5    0.07       0  4733.9   0.035       0  4879.8    0.07       0
  4987.2    0.07       0  4991.4    0.07       0  5139.8   0.035       0
  5330.4    0.07       0  5389.9   0.035       0
Bank Sta=4987.2,4991.4
Exp/Cntr=0.3,0.1

Type RM Length L Ch R = 1,55,0,0,0
BEGIN DESCRIPTION:
Chimney Creek 1151 1.0
END DESCRIPTION:
XS GIS Cut Line= 3
      1632497.32      7003057.05      1632704.24      7003582.69
      1633621.22      7003119.10
#Sta/Elev= 30
  4435.1 1518.60  4447.3 1518.81  4511.4 1517.13  4772.3 1514.44  4846.4 1512.91
  4856.8 1512.62  4954.9 1509.93  4983.6 1508.55  4994.8 1506.97  5010.0 1506.42
  5010.2 1505.92  5013.9 1505.92  5014.2 1506.42  5019.6 1507.54  5056.9 1510.19
  5087.3 1510.26  5101.7 1510.45  5108.7 1511.26  5114.3 1510.68  5174.7 1512.21
  5248.8 1512.75  5356.9 1514.39  5426.7 1514.96  5673.2 1519.17  5749.4 1521.58
  5771.7 1521.30  5860.9 1523.23  5888.8 1524.51  5949.3 1525.06  6027.5 1526.50
#Mann=11,-1,0
  4435.1    0.07       0  4846.4   0.035       0  4856.8    0.07       0
  4954.9   0.035       0  5010.0   0.035       0  5014.2   0.035       0
  5087.3    0.07       0  5174.7   0.035       0  5248.8    0.07       0
  5356.9   0.035       0  5949.3    0.16       0
Bank Sta=5010,5014.2
Exp/Cntr=0.3,0.1

Chan Stop Cuts=-1