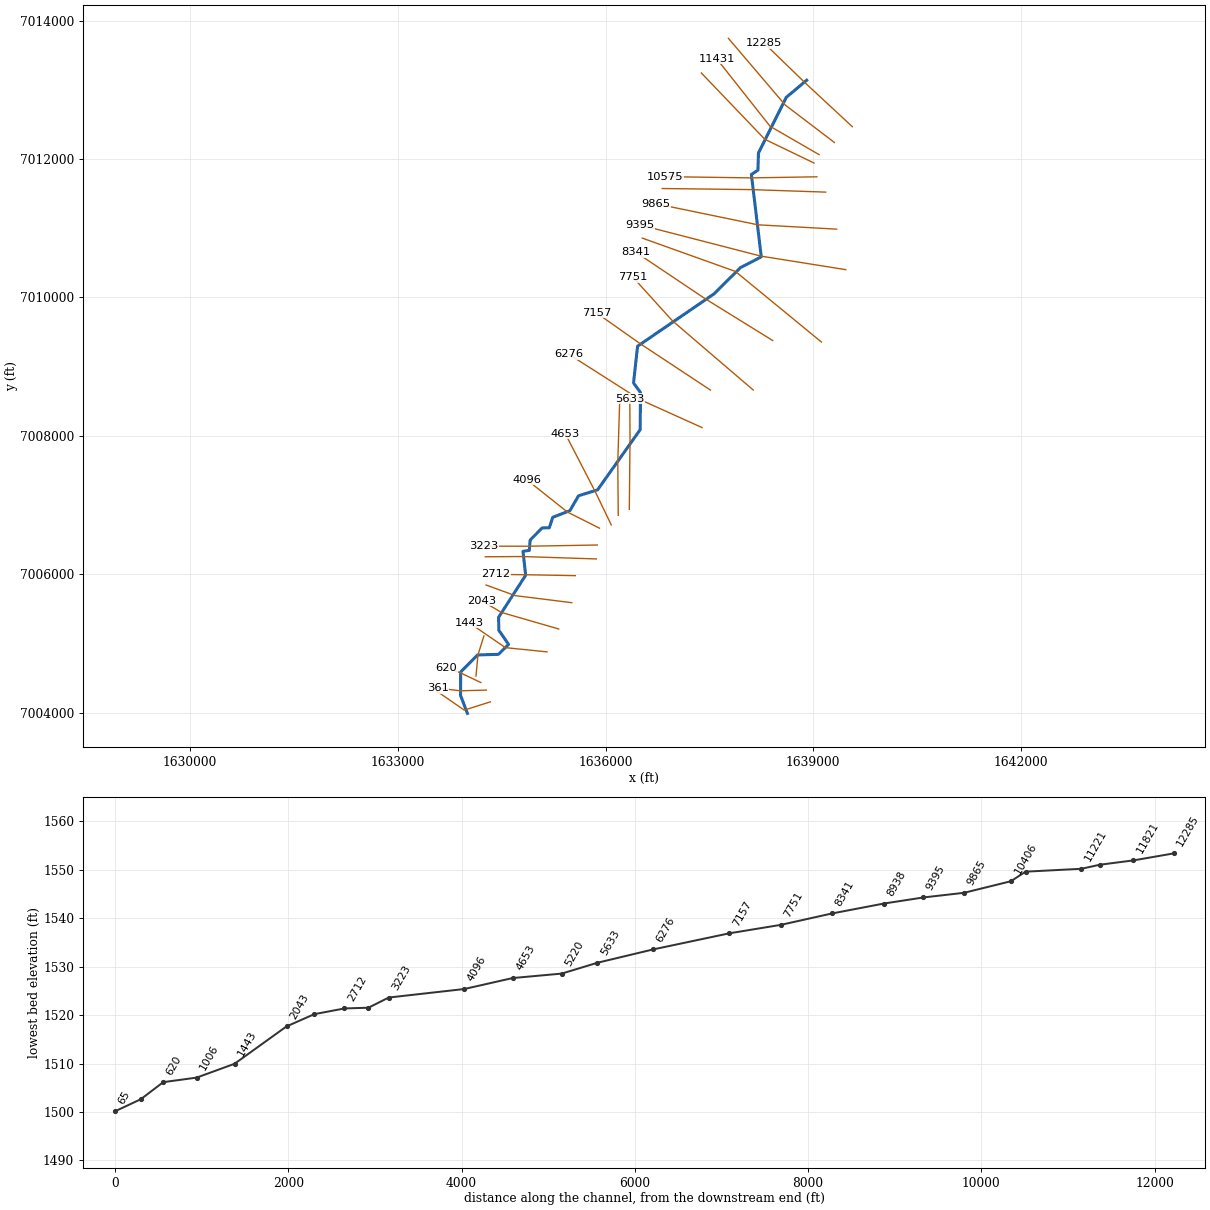
--- Chimney Creek 1152.prj (project) ---

Proj Title=Chimney Creek 1152 Base Level Engineering
Current Plan=p01
Default Exp/Contr=0.3,0.1
English Units
Geom File=g01
Flow File=f01
Plan File=p01
BEGIN DESCRIPTION:
Chimney Creek 1152
END DESCRIPTION:

--- Chimney Creek 1152.p01 (plan) ---

Plan Title=Multiple Run
Short Identifier=Multiple
Geom File=g01
Flow File=f01
Subcritical Flow
K Sum by GR= 0
Std Step Tol= 0.01
Critical Tol= 0.01
Num of Std Step Trials= 20
Max Error Tol= 0.3
Flow Tol Ratio= 0.001
Split Flow NTrial= 30
Split Flow Tol= 0.02
Split Flow Ratio= 0.02
Log Output Level= 0
Friction Slope Method= 1
Unsteady Friction Slope Method= 2
Unsteady Bridges Friction Slope Method= 1
Parabolic Critical Depth
Global Vel Dist=  1 , 1 , 1
Global Log Level= 0
CheckData=True
Encroach Param= -1, 0, 0, 0
BEGIN DESCRIPTION:
Multiple Run
END DESCRIPTION:

--- Chimney Creek 1152.f01 (steady flow) ---

Flow Title=Multiple
Number of Profiles=7
Profile Names=10-year,25-year,50-year,1pct_min,100-year,1pct_plu,500-year
River Rch & RM= Chimney Creek 11,Reach-1,12285
     192     259     313     189     376     751     549
River Rch & RM= Chimney Creek 11,Reach-1,11221
     253     346     422     256     511    1020     759
River Rch & RM= Chimney Creek 11,Reach-1,8938
     338     468     575     351     701    1398    1053
River Rch & RM= Chimney Creek 11,Reach-1,620
     530     750     935     579    1155    2305    1787
Boundary for River Rch & Prof#=Chimney Creek 11,Reach-1,1
Up Type=0
Dn Type=3
Dn Slope=0.005
Boundary for River Rch & Prof#=Chimney Creek 11,Reach-1,2
Up Type=0
Dn Type=3
Dn Slope=0.005
Boundary for River Rch & Prof#=Chimney Creek 11,Reach-1,3
Up Type=0
Dn Type=3
Dn Slope=0.005
Boundary for River Rch & Prof#=Chimney Creek 11,Reach-1,4
Up Type=0
Dn Type=3
Dn Slope=0.005
Boundary for River Rch & Prof#=Chimney Creek 11,Reach-1,5
Up Type=0
Dn Type=3
Dn Slope=0.005
Boundary for River Rch & Prof#=Chimney Creek 11,Reach-1,6
Up Type=0
Dn Type=3
Dn Slope=0.005
Boundary for River Rch & Prof#=Chimney Creek 11,Reach-1,7
Up Type=0
Dn Type=3
Dn Slope=0.005

--- Chimney Creek 1152.g01 (geometry) ---

Geom Title=Existing Conditions

River Reach=Chimney Creek 11,Reach-1
Reach XY= 30
      1638905.00      7013138.00      1638610.42      7012890.67
      1638208.75      7012086.45      1638201.52      7011839.26
      1638106.64      7011776.17      1638249.55      7010585.53
      1637948.94      7010429.86      1637564.68      7010048.78
      1636462.85      7009294.19      1636404.71      7008762.88
      1636503.94      7008627.56      1636501.46      7008089.46
      1635885.23      7007217.87      1635610.41      7007132.83
      1635485.27      7006917.49      1635237.87      7006821.55
      1635188.54      7006670.39      1635085.00      7006668.63
      1634910.47      7006490.44      1634899.88      7006343.11
      1634808.00      7006330.00      1634846.96      7005984.68
      1634456.20      7005377.50      1634458.54      7005189.46
      1634599.94      7004985.71      1634453.54      7004841.54
      1634152.52      7004832.60      1633908.54      7004586.53
      1633906.22      7004248.50      1634005.00      7003988.00

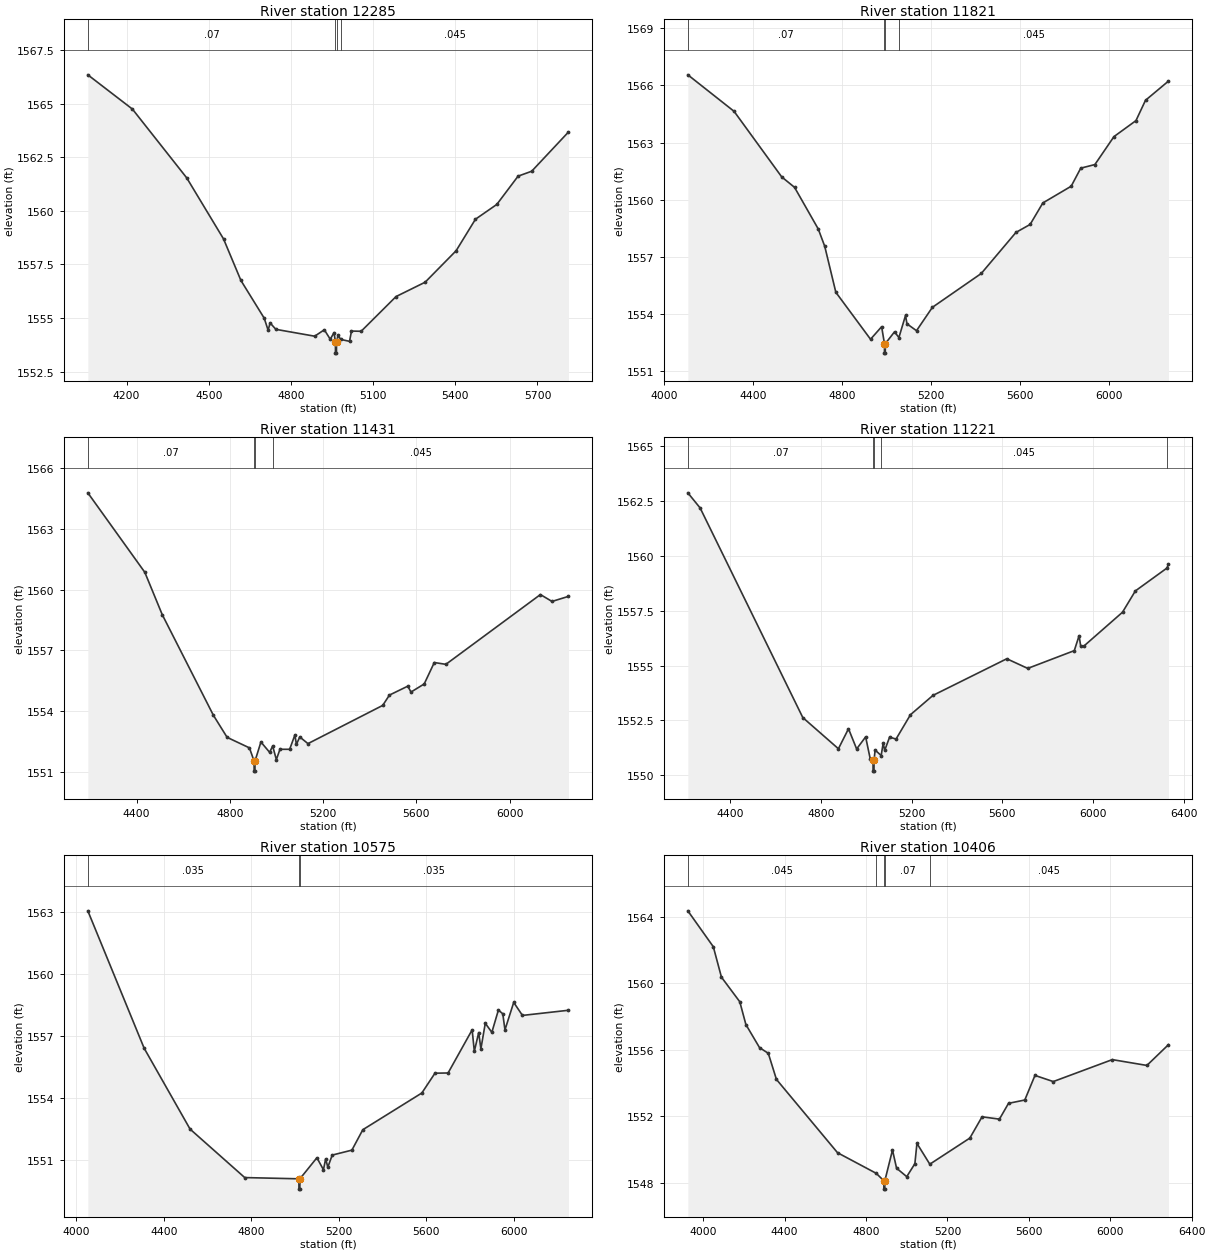
Type RM Length L Ch R = 1,12285,464,464,464
BEGIN DESCRIPTION:
Chimney Creek 1152 26.0
END DESCRIPTION:
XS GIS Cut Line= 3
      1639564.23      7012467.05      1638874.84      7013107.83
      1638291.23      7013674.12
#Sta/Elev= 30
  4058.8 1566.35  4221.6 1564.75  4419.8 1561.54  4554.2 1558.69  4617.7 1556.75
  4702.7 1554.99  4716.9 1554.43  4724.2 1554.77  4745.2 1554.47  4886.9 1554.15
  4922.1 1554.45  4943.6 1554.01  4957.8 1554.32  4962.6 1553.86  4962.8 1553.36
  4966.3 1553.36  4966.6 1553.86  4971.9 1554.19  4982.0 1554.00  5014.1 1553.91
  5021.2 1554.39  5056.5 1554.38  5183.8 1556.00  5290.0 1556.67  5403.2 1558.14
  5473.7 1559.61  5551.6 1560.30  5629.3 1561.62  5679.0 1561.85  5813.2 1563.68
#Mann=4,-1,0
  4058.8    0.07       0  4962.6   0.045       0  4966.6    0.07       0
  4982.0   0.045       0
Bank Sta=4962.6,4966.6
Exp/Cntr=0.3,0.1

Type RM Length L Ch R = 1,11821,390,390,390
BEGIN DESCRIPTION:
Mapping XS 0a0049bf
END DESCRIPTION:
XS GIS Cut Line= 3
      1639306.41      7012237.89      1638594.60      7012780.43
      1637774.70      7013743.49
#Sta/Elev= 30
  4106.2 1566.56  4314.0 1564.64  4528.1 1561.19  4585.8 1560.64  4692.3 1558.45
  4721.4 1557.54  4771.3 1555.12  4927.2 1552.65  4977.1 1553.31  4989.7 1552.42
  4989.9 1551.92  4993.4 1551.92  4993.7 1552.42  5035.0 1553.04  5054.7 1552.74
  5084.4 1553.90  5091.0 1553.46  5133.8 1553.10  5205.2 1554.33  5424.8 1556.11
  5580.7 1558.27  5644.4 1558.69  5701.5 1559.82  5828.9 1560.70  5871.8 1561.65
  5935.4 1561.84  6021.1 1563.31  6119.9 1564.15  6162.8 1565.22  6266.0 1566.23
#Mann=4,-1,0
  4106.2    0.07       0  4989.7    0.07       0  4993.7    0.07       0
  5054.7   0.045       0
Bank Sta=4989.7,4993.7
Exp/Cntr=0.3,0.1

Type RM Length L Ch R = 1,11431,210,210,210
BEGIN DESCRIPTION:
Mapping XS 4528c489
END DESCRIPTION:
XS GIS Cut Line= 3
      1639085.03      7012062.56      1638376.72      7012472.27
      1637605.90      7013447.95
#Sta/Elev= 30
  4190.6 1564.78  4435.1 1560.85  4509.7 1558.76  4729.3 1553.78  4788.1 1552.69
  4883.8 1552.17  4903.8 1551.52  4904.0 1551.02  4907.5 1551.02  4907.8 1551.52
  4933.1 1552.46  4970.4 1551.95  4983.5 1552.26  4999.3 1551.59  5014.8 1552.10
  5056.4 1552.10  5078.9 1552.81  5085.3 1552.34  5099.7 1552.71  5134.9 1552.38
  5455.6 1554.27  5484.4 1554.78  5563.0 1555.22  5576.9 1554.93  5633.5 1555.33
  5676.8 1556.39  5726.5 1556.30  6132.0 1559.75  6181.7 1559.41  6252.3 1559.66
#Mann=4,-1,0
  4190.6    0.07       0  4903.8   0.045       0  4907.8    0.07       0
  4983.5   0.045       0
Bank Sta=4903.8,4907.8
Exp/Cntr=0.3,0.1

Type RM Length L Ch R = 1,11221,646,646,646
BEGIN DESCRIPTION:
Mapping XS 98f4f6f1
END DESCRIPTION:
XS GIS Cut Line= 3
      1639012.12      7011941.02      1638300.33      7012284.77
      1637383.73      7013243.03
#Sta/Elev= 30
  4214.8 1562.87  4269.0 1562.18  4721.1 1552.63  4877.9 1551.21  4922.3 1552.12
  4958.2 1551.20  4997.8 1551.75  5018.4 1550.73  5030.3 1550.69  5030.6 1550.19
  5034.5 1550.19  5034.9 1550.69  5039.5 1551.15  5066.2 1550.90  5075.0 1551.46
  5081.9 1551.14  5103.3 1551.74  5131.6 1551.65  5195.2 1552.76  5294.2 1553.64
  5619.4 1555.31  5711.6 1554.87  5916.6 1555.68  5937.7 1556.36  5944.9 1555.88
  5959.1 1555.89  6128.9 1557.43  6185.5 1558.40  6324.3 1559.44  6331.3 1559.61
#Mann=5,-1,0
  4214.8    0.07       0  5030.3    0.07       0  5034.9    0.07       0
  5066.2   0.045       0  6324.3   0.035       0
Bank Sta=5030.3,5034.9
Exp/Cntr=0.3,0.1

Type RM Length L Ch R = 1,10575,169,169,169
BEGIN DESCRIPTION:
Mapping XS c69cdfb8
END DESCRIPTION:
XS GIS Cut Line= 3
      1639052.53      7011742.41      1638101.98      7011726.78
      1636854.59      7011745.01
#Sta/Elev= 30
  4051.9 1563.08  4309.5 1556.42  4519.5 1552.50  4769.5 1550.15  5017.2 1550.09
  5017.6 1549.59  5021.6 1549.59  5021.9 1550.09  5099.6 1551.11  5129.6 1550.53
  5139.6 1551.06  5149.6 1550.65  5169.6 1551.24  5259.6 1551.48  5309.6 1552.47
  5579.6 1554.25  5639.6 1555.21  5699.6 1555.22  5809.6 1557.31  5819.6 1556.27
  5839.6 1557.18  5849.6 1556.39  5869.7 1557.63  5899.7 1557.19  5929.7 1558.27
  5949.7 1558.09  5959.7 1557.31  5999.7 1558.64  6039.7 1558.01  6250.1 1558.26
#Mann=3,-1,0
  4051.9   0.035       0  5017.2   0.035       0  5021.9   0.035       0
Bank Sta=5017.2,5021.9
Exp/Cntr=0.3,0.1

Type RM Length L Ch R = 1,10406,541,541,541
BEGIN DESCRIPTION:
Mapping XS 77d02d51
END DESCRIPTION:
XS GIS Cut Line= 3
      1639180.13      7011521.05      1638099.38      7011557.51
      1636819.04      7011573.12
#Sta/Elev= 30
  3924.2 1564.36  4049.4 1562.20  4089.4 1560.37  4179.5 1558.89  4209.5 1557.52
  4276.6 1556.13  4319.6 1555.79  4359.6 1554.22  4659.8 1549.81  4850.1 1548.57
  4887.5 1548.12  4887.9 1547.62  4891.9 1547.62  4892.2 1548.12  4929.9 1549.97
  4949.9 1548.88  4999.9 1548.37  5039.9 1549.15  5050.0 1550.37  5113.3 1549.12
  5310.0 1550.69  5370.0 1551.97  5455.4 1551.83  5500.0 1552.78  5580.0 1552.98
  5630.0 1554.46  5720.0 1554.09  6010.0 1555.41  6180.0 1555.06  6286.0 1556.31
#Mann=5,-1,0
  3924.2   0.045       0  4850.1    0.07       0  4887.5    0.07       0
  4892.2    0.07       0  5113.3   0.045       0
Bank Sta=4887.5,4892.2
Exp/Cntr=0.3,0.1

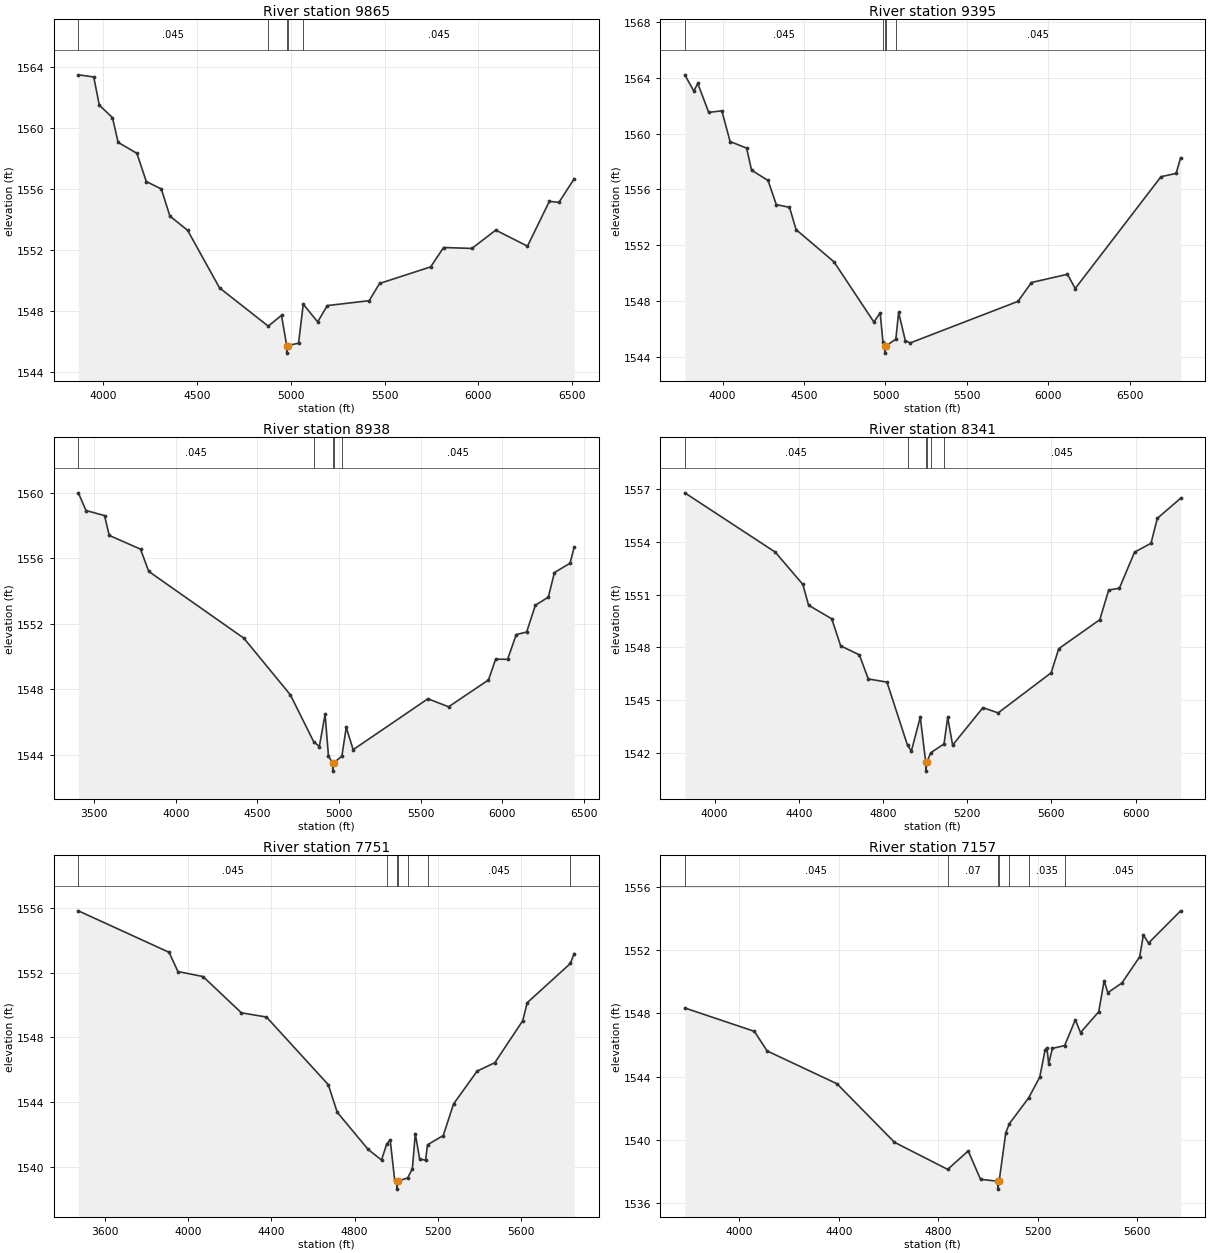
Type RM Length L Ch R = 1,9865,470,470,470
BEGIN DESCRIPTION:
Mapping XS 4f89c65f
END DESCRIPTION:
XS GIS Cut Line= 3
      1639336.84      7010986.11      1638201.38      7011048.61
      1636725.55      7011353.15
#Sta/Elev= 30
  3866.4 1563.49  3948.4 1563.35  3978.4 1561.50  4048.5 1560.68  4078.6 1559.06
  4178.7 1558.34  4228.8 1556.49  4308.9 1556.00  4354.8 1554.22  4449.1 1553.29
  4619.4 1549.51  4879.3 1547.00  4949.9 1547.71  4977.5 1545.73  4977.9 1545.23
  4982.3 1545.73  5040.7 1545.88  5065.8 1548.44  5142.8 1547.28  5193.9 1548.35
  5417.3 1548.67  5472.7 1549.80  5745.3 1550.89  5814.3 1552.16  5965.1 1552.10
  6092.4 1553.30  6261.6 1552.25  6378.3 1555.19  6429.4 1555.12  6510.5 1556.67
#Mann=5,-1,0
  3866.4   0.045       0  4879.3    0.07       0  4977.5    0.07       0
  4982.3    0.07       0  5065.8   0.045       0
Bank Sta=4977.5,4982.3
Exp/Cntr=0.3,0.1

Type RM Length L Ch R = 1,9395,457,457,457
BEGIN DESCRIPTION:
Mapping XS d2c48e7b
END DESCRIPTION:
XS GIS Cut Line= 3
      1639469.65      7010400.60      1638245.65      7010595.92
      1636498.28      7011046.85
#Sta/Elev= 30
  3768.1 1564.21  3823.4 1563.05  3847.8 1563.59  3914.9 1561.52  3995.6 1561.63
  4046.2 1559.43  4147.5 1558.96  4177.9 1557.38  4279.1 1556.64  4329.8 1554.91
  4410.8 1554.72  4451.3 1553.12  4684.2 1550.81  4928.9 1546.50  4967.7 1547.15
  4984.8 1545.04  4995.7 1544.77  4996.0 1544.27  5000.6 1544.77  5063.8 1545.27
  5080.8 1547.19  5121.9 1545.17  5151.8 1545.00  5813.8 1547.98  5896.4 1549.33
  6117.5 1549.92  6165.0 1548.90  6691.7 1556.91  6784.6 1557.15  6812.2 1558.27
#Mann=5,-1,0
  3768.1   0.045       0  4984.8    0.07       0  4995.7    0.07       0
  5000.6    0.07       0  5063.8   0.045       0
Bank Sta=4995.7,5000.6
Exp/Cntr=0.3,0.1

Type RM Length L Ch R = 1,8938,597,597,597
BEGIN DESCRIPTION:
Mapping XS 9c58529a
END DESCRIPTION:
XS GIS Cut Line= 3
      1639118.08      7009354.57      1637876.72      7010374.57
      1636531.23      7010856.34
#Sta/Elev= 30
  3403.8 1560.01  3450.8 1558.93  3564.2 1558.62  3592.9 1557.41  3784.5 1556.57
  3834.9 1555.21  4417.3 1551.13  4702.1 1547.67  4844.7 1544.81  4879.4 1544.51
  4914.6 1546.48  4935.4 1543.92  4961.5 1543.51  4961.9 1543.01  4966.6 1543.51
  5017.2 1543.92  5044.2 1545.68  5086.6 1544.32  5544.2 1547.43  5670.8 1546.94
  5915.1 1548.58  5959.0 1549.85  6032.0 1549.84  6085.1 1551.35  6148.8 1551.51
  6201.9 1553.14  6281.5 1553.64  6318.8 1555.14  6414.4 1555.71  6439.6 1556.69
#Mann=5,-1,0
  3403.8   0.045       0  4844.7    0.07       0  4961.5    0.07       0
  4966.6    0.07       0  5017.2   0.045       0
Bank Sta=4961.5,4966.6
Exp/Cntr=0.3,0.1

Type RM Length L Ch R = 1,8341,590,590,590
BEGIN DESCRIPTION:
Mapping XS 0278753a
END DESCRIPTION:
XS GIS Cut Line= 3
      1638414.61      7009376.31      1637438.93      7009980.47
      1636436.28      7010653.53
#Sta/Elev= 30
  3858.5 1556.79  4288.2 1553.42  4419.4 1551.58  4446.5 1550.40  4556.4 1549.63
  4599.0 1548.09  4687.6 1547.58  4730.1 1546.21  4818.8 1546.03  4916.4 1542.44
  4934.6 1542.11  4977.1 1544.04  5002.9 1541.47  5003.3 1540.97  5008.1 1541.47
  5026.4 1542.01  5089.9 1542.52  5107.2 1544.03  5130.7 1542.45  5274.8 1544.58
  5346.8 1544.28  5598.8 1546.56  5634.8 1547.93  5829.8 1549.58  5871.9 1551.26
  5922.9 1551.37  5994.9 1553.42  6073.0 1553.92  6103.0 1555.34  6213.7 1556.48
#Mann=6,-1,0
  3858.5   0.045       0  4916.4   0.035       0  5002.9   0.035       0
  5008.1   0.035       0  5026.4    0.07       0  5089.9   0.045       0
Bank Sta=5002.9,5008.1
Exp/Cntr=0.3,0.1

Type RM Length L Ch R = 1,7751,594,594,594
BEGIN DESCRIPTION:
Mapping XS 92d0ba00
END DESCRIPTION:
XS GIS Cut Line= 3
      1638133.41      7008660.99      1636966.71      7009661.03
      1636397.28      7010289.48
#Sta/Elev= 30
  3471.1 1555.81  3907.3 1553.25  3950.1 1552.06  4070.9 1551.75  4255.3 1549.51
  4376.0 1549.25  4673.4 1545.07  4716.2 1543.37  4865.1 1541.07  4929.2 1540.42
  4953.9 1541.39  4970.9 1541.67  4992.8 1539.16  5002.7 1539.12  5003.2 1538.62
  5008.4 1539.12  5054.9 1539.31  5077.6 1539.88  5091.8 1542.05  5112.7 1540.48
  5141.1 1540.41  5150.5 1541.36  5226.3 1541.93  5275.6 1543.88  5389.2 1545.91
  5474.3 1546.43  5608.8 1549.03  5629.7 1550.13  5837.7 1552.56  5855.8 1553.17
#Mann=7,-1,0
  3471.1   0.045       0  4953.9   0.035       0  5002.7   0.035       0
  5008.4   0.035       0  5054.9    0.07       0  5150.5   0.045       0
  5837.7   0.035       0
Bank Sta=5002.7,5008.4
Exp/Cntr=0.3,0.1

Type RM Length L Ch R = 1,7157,881,881,881
BEGIN DESCRIPTION:
Mapping XS fc5211a7
END DESCRIPTION:
XS GIS Cut Line= 3
      1637515.31      7008660.17      1636491.02      7009337.24
      1635865.98      7009778.24
#Sta/Elev= 30
  3781.2 1548.35  4060.8 1546.87  4112.0 1545.63  4392.9 1543.55  4623.6 1539.85
  4837.7 1538.13  4920.4 1539.30  4969.7 1537.50  5038.8 1537.38  5039.2 1536.88
  5044.6 1537.38  5071.3 1540.46  5086.0 1541.03  5163.3 1542.66  5208.0 1543.98
  5228.9 1545.67  5236.7 1545.83  5243.7 1544.81  5258.5 1545.79  5307.8 1545.97
  5350.8 1547.60  5371.7 1546.79  5444.8 1548.11  5466.6 1550.07  5481.4 1549.32
  5538.0 1549.93  5609.4 1551.59  5624.2 1552.97  5645.1 1552.46  5774.0 1554.50
#Mann=7,-1,0
  3781.2   0.045       0  4837.7    0.07       0  5038.8    0.07       0
  5044.6    0.07       0  5086.0   0.045       0  5163.3   0.035       0
  5307.8   0.045       0
Bank Sta=5038.8,5044.6
Exp/Cntr=0.3,0.1

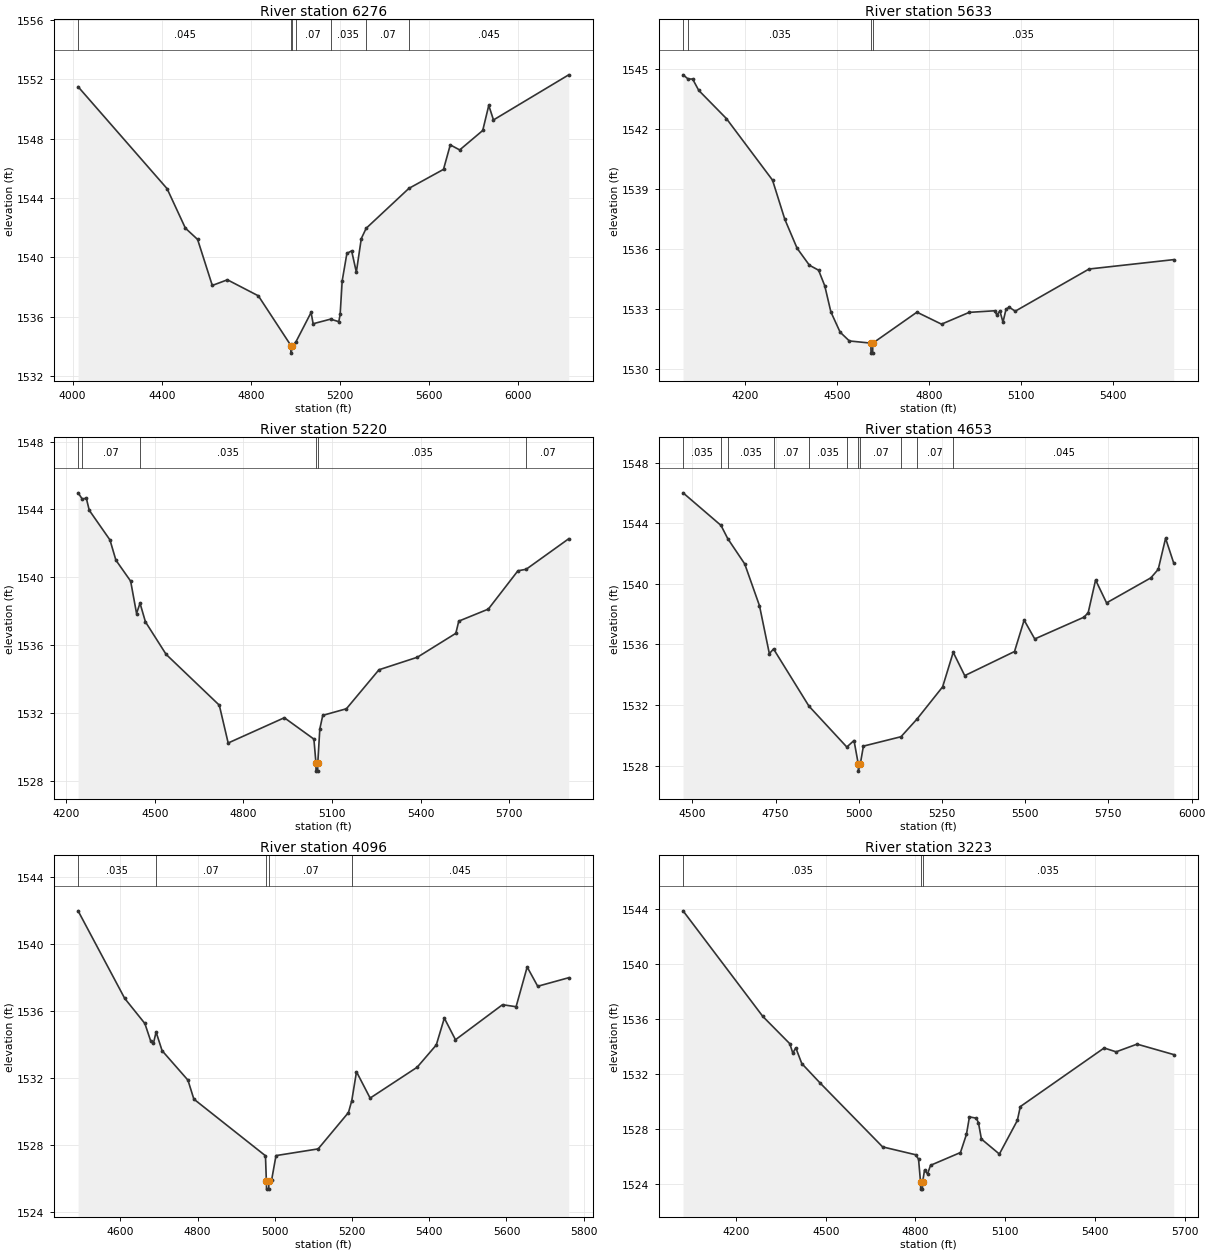
Type RM Length L Ch R = 1,6276,643,643,643
BEGIN DESCRIPTION:
Mapping XS 97531cd7
END DESCRIPTION:
XS GIS Cut Line= 3
      1637393.78      7008118.50      1636494.49      7008524.74
      1635470.20      7009177.51
#Sta/Elev= 30
  4024.8 1551.50  4424.2 1544.63  4506.3 1541.97  4561.1 1541.21  4627.0 1538.11
  4694.9 1538.49  4833.7 1537.41  4980.3 1534.05  4980.8 1533.55  4986.3 1534.05
  5002.3 1534.31  5070.3 1536.29  5079.5 1535.53  5157.8 1535.84  5194.6 1535.67
  5200.7 1536.16  5209.8 1538.42  5231.0 1540.27  5252.2 1540.44  5273.3 1539.01
  5295.6 1541.27  5317.4 1541.96  5509.2 1544.65  5664.4 1545.93  5694.8 1547.58
  5737.1 1547.24  5840.4 1548.55  5867.5 1550.24  5888.7 1549.26  6226.2 1552.30
#Mann=7,-1,0
  4024.8   0.045       0  4980.3   0.045       0  4986.3   0.045       0
  5002.3    0.07       0  5157.8   0.035       0  5317.4    0.07       0
  5509.2   0.045       0
Bank Sta=4980.3,4986.3
Exp/Cntr=0.3,0.1

Type RM Length L Ch R = 1,5633,413,413,413
BEGIN DESCRIPTION:
Mapping XS 9a733995
END DESCRIPTION:
XS GIS Cut Line= 3
      1636343.71      7006936.91      1636354.12      7007950.78
      1636350.66      7008533.54
#Sta/Elev= 30
  3999.5 1544.73  4016.1 1544.52  4030.6 1544.52  4050.6 1543.95  4140.6 1542.54
  4290.6 1539.46  4330.6 1537.50  4370.6 1536.05  4410.6 1535.20  4440.6 1534.95
  4460.6 1534.17  4480.6 1532.86  4510.6 1531.85  4540.6 1531.41  4610.7 1531.30
  4611.2 1530.80  4616.5 1530.80  4617.0 1531.30  4760.6 1532.85  4840.6 1532.25
  4930.6 1532.84  5013.4 1532.92  5020.6 1532.71  5030.6 1532.91  5040.6 1532.35
  5050.6 1533.00  5060.6 1533.10  5080.6 1532.90  5320.7 1535.01  5596.2 1535.48
#Mann=4,-1,0
  3999.5    0.07       0  4016.1   0.035       0  4610.7   0.035       0
  4617.0   0.035       0
Bank Sta=4610.7,4617
Exp/Cntr=0.3,0.1

Type RM Length L Ch R = 1,5220,567,567,567
BEGIN DESCRIPTION:
Mapping XS 1c107f6c
END DESCRIPTION:
XS GIS Cut Line= 3
      1636183.99      7006850.08      1636177.04      7007613.98
      1636204.82      7008509.82
#Sta/Elev= 30
  4240.5 1544.98  4254.5 1544.62  4268.4 1544.66  4278.4 1543.95  4348.4 1542.20
  4368.4 1541.01  4418.4 1539.77  4438.4 1537.86  4450.1 1538.47  4468.4 1537.37
  4538.4 1535.45  4718.4 1532.45  4748.4 1530.22  4938.4 1531.71  5038.5 1530.45
  5045.3 1529.06  5045.8 1528.56  5051.2 1528.56  5051.7 1529.06  5058.5 1531.05
  5068.5 1531.85  5148.5 1532.24  5258.6 1534.54  5388.6 1535.28  5518.7 1536.69
  5528.7 1537.41  5628.7 1538.12  5728.8 1540.38  5756.8 1540.47  5900.7 1542.27
#Mann=6,-1,0
  4240.5   0.035       0  4254.5    0.07       0  4450.1   0.035       0
  5045.3   0.035       0  5051.7   0.035       0  5756.8    0.07       0
Bank Sta=5045.3,5051.7
Exp/Cntr=0.3,0.1

Type RM Length L Ch R = 1,4653,557,557,557
BEGIN DESCRIPTION:
Mapping XS e97183a0
END DESCRIPTION:
XS GIS Cut Line= 3
      1636083.31      7006711.16      1635850.65      7007193.84
      1635420.10      7008027.16
#Sta/Elev= 30
  4472.3 1546.00  4586.3 1543.85  4606.5 1542.98  4657.5 1541.31  4701.9 1538.55
  4731.5 1535.39  4744.1 1535.70  4850.4 1531.93  4964.2 1529.23  4985.8 1529.66
  4998.4 1528.14  4998.9 1527.64  5004.9 1528.14  5014.0 1529.29  5127.0 1529.91
  5175.2 1531.08  5252.0 1533.20  5283.8 1535.48  5318.4 1533.94  5467.9 1535.53
  5496.8 1537.60  5528.7 1536.36  5676.9 1537.80  5689.3 1538.10  5711.5 1540.25
  5744.4 1538.74  5877.4 1540.39  5899.6 1540.95  5921.7 1543.00  5946.1 1541.37
#Mann=11,-1,0
  4472.3   0.035       0  4586.3    0.07       0  4606.5   0.035       0
  4744.1    0.07       0  4850.4   0.035       0  4964.2    0.07       0
  4998.4    0.07       0  5004.9    0.07       0  5127.0   0.045       0
  5175.2    0.07       0  5283.8   0.045       0
Bank Sta=4998.4,5004.9
Exp/Cntr=0.3,0.1

Type RM Length L Ch R = 1,4096,873,873,873
BEGIN DESCRIPTION:
Mapping XS 4444d0ab
END DESCRIPTION:
XS GIS Cut Line= 3
      1635912.82      7006664.32      1635451.00      7006896.96
      1634860.70      7007365.73
#Sta/Elev= 30
  4490.3 1541.98  4611.0 1536.76  4663.3 1535.26  4678.2 1534.23  4685.6 1534.09
  4692.4 1534.75  4707.9 1533.64  4774.9 1531.88  4790.2 1530.75  4975.7 1527.37
  4978.0 1525.88  4978.5 1525.38  4984.1 1525.38  4984.6 1525.88  4991.7 1525.93
  5003.0 1527.38  5112.2 1527.78  5190.7 1529.95  5199.2 1530.65  5211.5 1532.38
  5246.8 1530.81  5368.6 1532.65  5418.2 1533.98  5439.0 1535.58  5467.9 1534.29
  5589.7 1536.38  5624.9 1536.26  5653.6 1538.63  5680.9 1537.48  5761.2 1537.99
#Mann=5,-1,0
  4490.3   0.035       0  4692.4    0.07       0  4978.0    0.07       0
  4984.6    0.07       0  5199.2   0.045       0
Bank Sta=4978,4984.6
Exp/Cntr=0.3,0.1

Type RM Length L Ch R = 1,3223,234,234,234
BEGIN DESCRIPTION:
Mapping XS fc029e88
END DESCRIPTION:
XS GIS Cut Line= 3
      1635881.58      7006421.27      1634902.39      7006403.91
      1634242.63      7006403.91
#Sta/Elev= 30
  4023.5 1543.85  4290.1 1536.17  4380.1 1534.19  4390.1 1533.51  4400.1 1533.89
  4420.1 1532.75  4480.2 1531.36  4690.2 1526.69  4800.2 1526.12  4810.2 1525.80
  4816.9 1524.12  4817.4 1523.62  4823.1 1523.62  4823.6 1524.12  4830.2 1525.00
  4840.2 1524.72  4850.2 1525.35  4950.2 1526.28  4970.2 1527.60  4980.2 1528.87
  5002.8 1528.78  5010.2 1528.46  5020.2 1527.26  5080.2 1526.17  5140.2 1528.61
  5150.2 1529.62  5430.2 1533.88  5470.2 1533.60  5540.2 1534.16  5662.6 1533.40
#Mann=3,-1,0
  4023.5   0.035       0  4816.9   0.035       0  4823.6   0.035       0
Bank Sta=4816.9,4823.6
Exp/Cntr=0.3,0.1

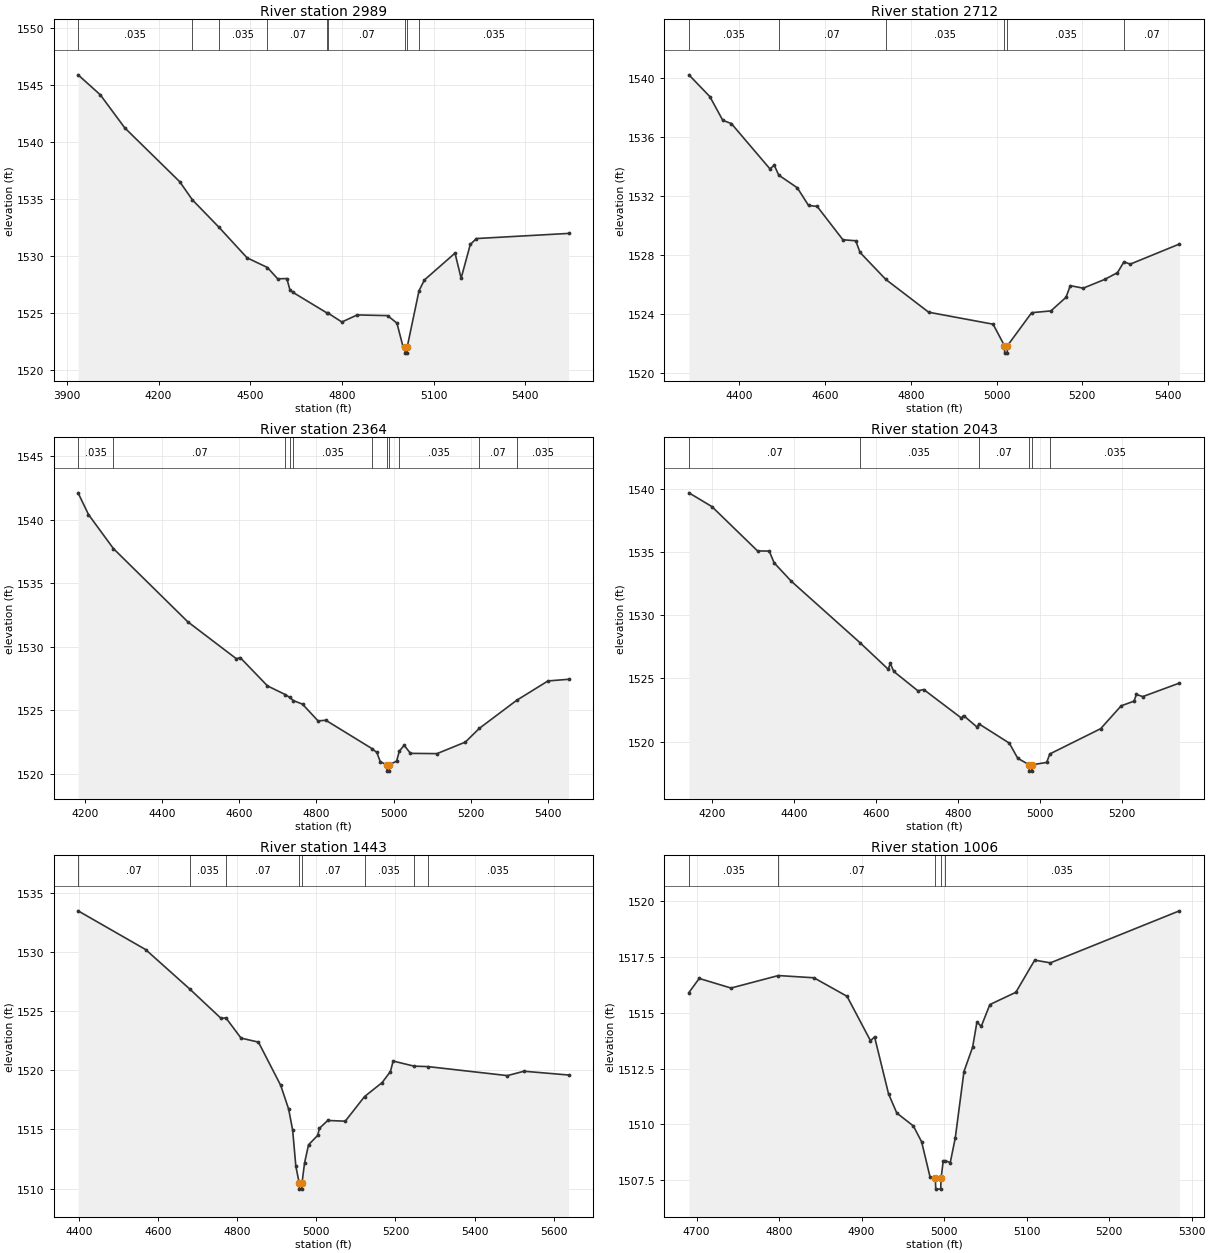
Type RM Length L Ch R = 1,2989,277,277,277
BEGIN DESCRIPTION:
Mapping XS da7ccc33
END DESCRIPTION:
XS GIS Cut Line= 3
      1635867.62      7006219.88      1634801.69      7006254.60
      1634263.50      7006251.13
#Sta/Elev= 30
  3936.6 1545.93  4009.3 1544.18  4089.3 1541.28  4269.4 1536.55  4310.4 1534.97
  4396.9 1532.58  4489.5 1529.88  4556.1 1529.03  4589.6 1528.04  4619.6 1528.06
  4629.6 1527.08  4639.6 1526.85  4752.4 1525.02  4754.5 1525.03  4799.7 1524.25
  4849.7 1524.87  4949.3 1524.81  4979.8 1524.15  4998.9 1522.17  5006.4 1522.02
  5006.9 1521.52  5012.6 1521.52  5013.1 1522.02  5052.0 1526.99  5069.8 1527.94
  5169.8 1530.29  5189.8 1528.09  5219.8 1531.05  5239.8 1531.57  5541.3 1532.02
#Mann=9,-1,0
  3936.6   0.035       0  4310.4    0.07       0  4396.9   0.035       0
  4556.1    0.07       0  4752.4   0.035       0  4754.5    0.07       0
  5006.4    0.07       0  5013.1    0.07       0  5052.0   0.035       0
Bank Sta=5006.4,5013.1
Exp/Cntr=0.3,0.1

Type RM Length L Ch R = 1,2712,348,348,348
BEGIN DESCRIPTION:
Mapping XS 7c30533c
END DESCRIPTION:
XS GIS Cut Line= 3
      1635563.86      7005978.45      1634845.11      7005991.47
      1634420.61      7005996.68
#Sta/Elev= 30
  4282.9 1540.22  4331.8 1538.74  4361.8 1537.14  4381.8 1536.92  4471.8 1533.85
  4481.8 1534.10  4492.2 1533.43  4535.5 1532.57  4561.8 1531.37  4581.8 1531.31
  4641.8 1529.05  4671.8 1528.98  4681.8 1528.19  4741.9 1526.36  4841.9 1524.14
  4991.9 1523.33  5018.5 1521.87  5019.0 1521.37  5024.8 1521.37  5025.3 1521.87
  5081.9 1524.11  5126.7 1524.23  5161.9 1525.15  5171.9 1525.94  5201.9 1525.77
  5251.9 1526.36  5281.9 1526.82  5296.9 1527.55  5311.9 1527.40  5426.3 1528.76
#Mann=6,-1,0
  4282.9   0.035       0  4492.2    0.07       0  4741.9   0.035       0
  5018.5   0.035       0  5025.3   0.035       0  5296.9    0.07       0
Bank Sta=5018.5,5025.3
Exp/Cntr=0.3,0.1

Type RM Length L Ch R = 1,2364,321,321,321
BEGIN DESCRIPTION:
Mapping XS bfc442db
END DESCRIPTION:
XS GIS Cut Line= 3
      1635511.82      7005587.82      1634696.68      7005689.39
      1634274.83      7005843.02
#Sta/Elev= 30
  4182.6 1542.13  4209.6 1540.42  4274.3 1537.73  4466.9 1531.96  4592.6 1529.05
  4602.6 1529.14  4673.2 1526.91  4719.6 1526.22  4730.7 1526.00  4740.5 1525.75
  4763.9 1525.47  4804.2 1524.15  4824.3 1524.20  4943.6 1521.97  4956.4 1521.66
  4965.4 1520.93  4982.2 1520.69  4982.7 1520.19  4988.5 1520.19  4989.0 1520.69
  5007.6 1520.98  5014.8 1521.77  5027.1 1522.23  5043.5 1521.59  5112.3 1521.57
  5185.7 1522.48  5222.2 1523.57  5318.9 1525.78  5399.7 1527.30  5453.0 1527.43
#Mann=11,-1,0
  4182.6   0.035       0  4274.3    0.07       0  4719.6   0.035       0
  4730.7    0.07       0  4740.5   0.035       0  4943.6    0.07       0
  4982.2    0.07       0  4989.0    0.07       0  5014.8   0.035       0
  5222.2    0.07       0  5318.9   0.035       0
Bank Sta=4982.2,4989
Exp/Cntr=0.3,0.1

Type RM Length L Ch R = 1,2043,600,600,600
BEGIN DESCRIPTION:
Mapping XS b00a8793
END DESCRIPTION:
XS GIS Cut Line= 3
      1635324.33      7005207.60      1634496.16      7005447.20
      1634209.84      7005616.38
#Sta/Elev= 30
  4144.5 1539.69  4200.5 1538.60  4311.7 1535.09  4340.1 1535.08  4352.0 1534.15
  4393.6 1532.70  4561.4 1527.82  4629.8 1525.73  4635.0 1526.18  4643.5 1525.55
  4702.2 1524.02  4716.4 1524.12  4808.2 1521.86  4813.4 1522.06  4847.0 1521.13
  4850.5 1521.41  4924.7 1519.88  4945.4 1518.68  4973.2 1518.16  4973.7 1517.66
  4979.6 1517.66  4980.1 1518.16  5015.9 1518.35  5023.5 1519.02  5147.4 1521.02
  5197.3 1522.83  5228.6 1523.20  5234.4 1523.73  5250.0 1523.56  5339.2 1524.63
#Mann=6,-1,0
  4144.5    0.07       0  4561.4   0.035       0  4850.5    0.07       0
  4973.2    0.07       0  4980.1    0.07       0  5023.5   0.035       0
Bank Sta=4973.2,4980.1
Exp/Cntr=0.3,0.1

Type RM Length L Ch R = 1,1443,437,437,437
BEGIN DESCRIPTION:
Chimney Creek 1152 3.0
END DESCRIPTION:
XS GIS Cut Line= 3
      1635154.97      7004876.89      1634555.00      7004938.00
      1634028.74      7005297.85
#Sta/Elev= 30
  4397.3 1533.46  4568.1 1530.19  4679.9 1526.85  4759.1 1524.37  4771.2 1524.42
  4809.4 1522.71  4853.5 1522.37  4909.9 1518.71  4930.0 1516.70  4940.1 1514.92
  4948.1 1511.89  4956.7 1510.45  4957.2 1509.95  4963.1 1509.95  4963.6 1510.45
  4970.2 1512.17  4980.3 1513.70  5003.4 1514.49  5007.8 1515.09  5028.8 1515.75
  5073.1 1515.69  5121.9 1517.77  5166.3 1518.95  5187.3 1519.88  5194.2 1520.77
  5247.0 1520.34  5282.5 1520.30  5483.2 1519.54  5525.2 1519.91  5637.9 1519.59
#Mann=8,-1,0
  4397.3    0.07       0  4679.9   0.035       0  4771.2    0.07       0
  4956.7    0.07       0  4963.6    0.07       0  5121.9   0.035       0
  5247.0    0.07       0  5282.5   0.035       0
Bank Sta=4956.7,4963.6
Exp/Cntr=0.3,0.1

Type RM Length L Ch R = 1,1006,386,386,386
BEGIN DESCRIPTION:
Chimney Creek 1152 2.0
END DESCRIPTION:
XS GIS Cut Line= 3
      1634129.15      7004527.19      1634158.02      7004835.04
      1634243.73      7005107.06
#Sta/Elev= 30
  4690.8 1515.91  4703.3 1516.54  4741.8 1516.11  4799.2 1516.67  4842.3 1516.57
  4882.4 1515.74  4910.8 1513.75  4915.8 1513.92  4932.7 1511.37  4942.7 1510.51
  4962.8 1509.93  4972.8 1509.22  4982.9 1507.66  4989.4 1507.60  4989.9 1507.10
  4995.9 1507.10  4996.4 1507.60  4999.0 1508.37  5001.6 1508.37  5007.5 1508.29
  5013.6 1509.40  5024.1 1512.37  5034.6 1513.46  5039.8 1514.58  5045.1 1514.40
  5055.5 1515.37  5087.0 1515.92  5109.8 1517.36  5128.9 1517.24  5285.2 1519.57
#Mann=5,-1,0
  4690.8   0.035       0  4799.2    0.07       0  4989.4    0.07       0
  4996.4    0.07       0  5001.6   0.035       0
Bank Sta=4989.4,4996.4
Exp/Cntr=0.3,0.1

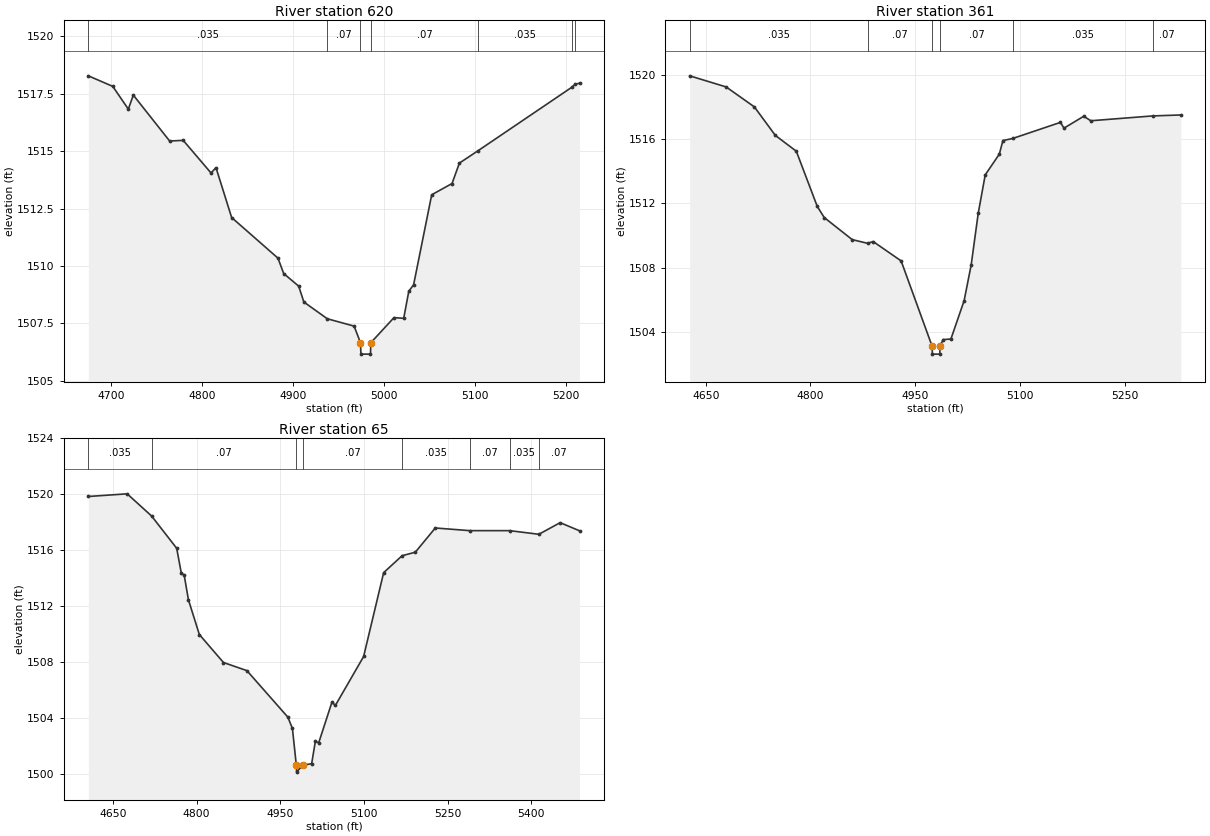
Type RM Length L Ch R = 1,620,259,259,259
BEGIN DESCRIPTION:
Mapping XS 973c0676
END DESCRIPTION:
XS GIS Cut Line= 3
      1634199.34      7004433.97      1633902.48      7004574.58
      1633703.28      7004647.49
#Sta/Elev= 30
  4674.8 1518.28  4701.7 1517.82  4718.8 1516.83  4724.3 1517.44  4764.3 1515.44
  4779.2 1515.47  4809.8 1514.05  4815.3 1514.28  4832.5 1512.11  4883.5 1510.34
  4889.8 1509.67  4906.3 1509.12  4912.0 1508.43  4937.8 1507.70  4967.3 1507.38
  4974.3 1506.66  4974.8 1506.16  4985.3 1506.16  4985.8 1506.66  5011.2 1507.75
  5021.9 1507.72  5027.5 1508.90  5032.8 1509.18  5052.7 1513.10  5075.1 1513.59
  5083.2 1514.48  5103.8 1515.02  5207.2 1517.79  5210.4 1517.91  5215.4 1517.96
#Mann=7,-1,0
  4674.8   0.035       0  4937.8    0.07       0  4974.3    0.07       0
  4985.8    0.07       0  5103.8   0.035       0  5207.2    0.07       0
  5210.4   0.035       0
Bank Sta=4974.3,4985.8
Exp/Cntr=0.3,0.1

Type RM Length L Ch R = 1,361,296,296,296
BEGIN DESCRIPTION:
Mapping XS 84cc71fc
END DESCRIPTION:
XS GIS Cut Line= 3
      1634277.53      7004324.58      1633903.78      7004314.17
      1633577.00      7004353.22
#Sta/Elev= 30
  4627.1 1519.92  4679.3 1519.23  4719.7 1517.99  4749.7 1516.22  4779.7 1515.24
  4809.7 1511.81  4819.7 1511.12  4859.7 1509.75  4881.8 1509.52  4889.7 1509.63
  4929.7 1508.43  4974.0 1503.14  4974.5 1502.64  4985.0 1502.64  4985.5 1503.14
  4989.8 1503.54  5001.0 1503.58  5019.9 1505.96  5030.0 1508.18  5040.1 1511.39
  5050.1 1513.77  5070.3 1515.06  5075.4 1515.90  5089.4 1516.03  5157.8 1517.03
  5162.8 1516.67  5191.1 1517.41  5201.2 1517.13  5289.6 1517.43  5330.1 1517.49
#Mann=6,-1,0
  4627.1   0.035       0  4881.8    0.07       0  4974.0    0.07       0
  4985.5    0.07       0  5089.4   0.035       0  5289.6    0.07       0
Bank Sta=4974,4985.5
Exp/Cntr=0.3,0.1

Type RM Length L Ch R = 1,65,0,0,0
BEGIN DESCRIPTION:
Chimney Creek 1152 1.0
END DESCRIPTION:
XS GIS Cut Line= 3
      1634336.08      7004154.01      1633960.15      7004035.42
      1633559.38      7004311.22
#Sta/Elev= 30
  4605.8 1519.85  4675.4 1520.04  4719.1 1518.46  4764.2 1516.15  4772.4 1514.39
  4777.7 1514.22  4785.2 1512.48  4804.8 1509.99  4848.1 1507.99  4890.1 1507.41
  4963.5 1504.09  4971.7 1503.28  4978.7 1500.66  4979.2 1500.16  4990.2 1500.66
  5006.2 1500.76  5012.8 1502.35  5018.9 1502.26  5042.6 1505.16  5048.7 1504.92
  5099.4 1508.42  5135.3 1514.41  5168.4 1515.62  5192.1 1515.87  5227.9 1517.60
  5289.7 1517.41  5361.3 1517.41  5413.6 1517.15  5451.8 1517.98  5486.5 1517.40
#Mann=8,-1,0
  4605.8   0.035       0  4719.1    0.07       0  4978.7    0.07       0
  4990.2    0.07       0  5168.4   0.035       0  5289.7    0.07       0
  5361.3   0.035       0  5413.6    0.07       0
Bank Sta=4978.7,4990.2
Exp/Cntr=0.3,0.1

Chan Stop Cuts=-1