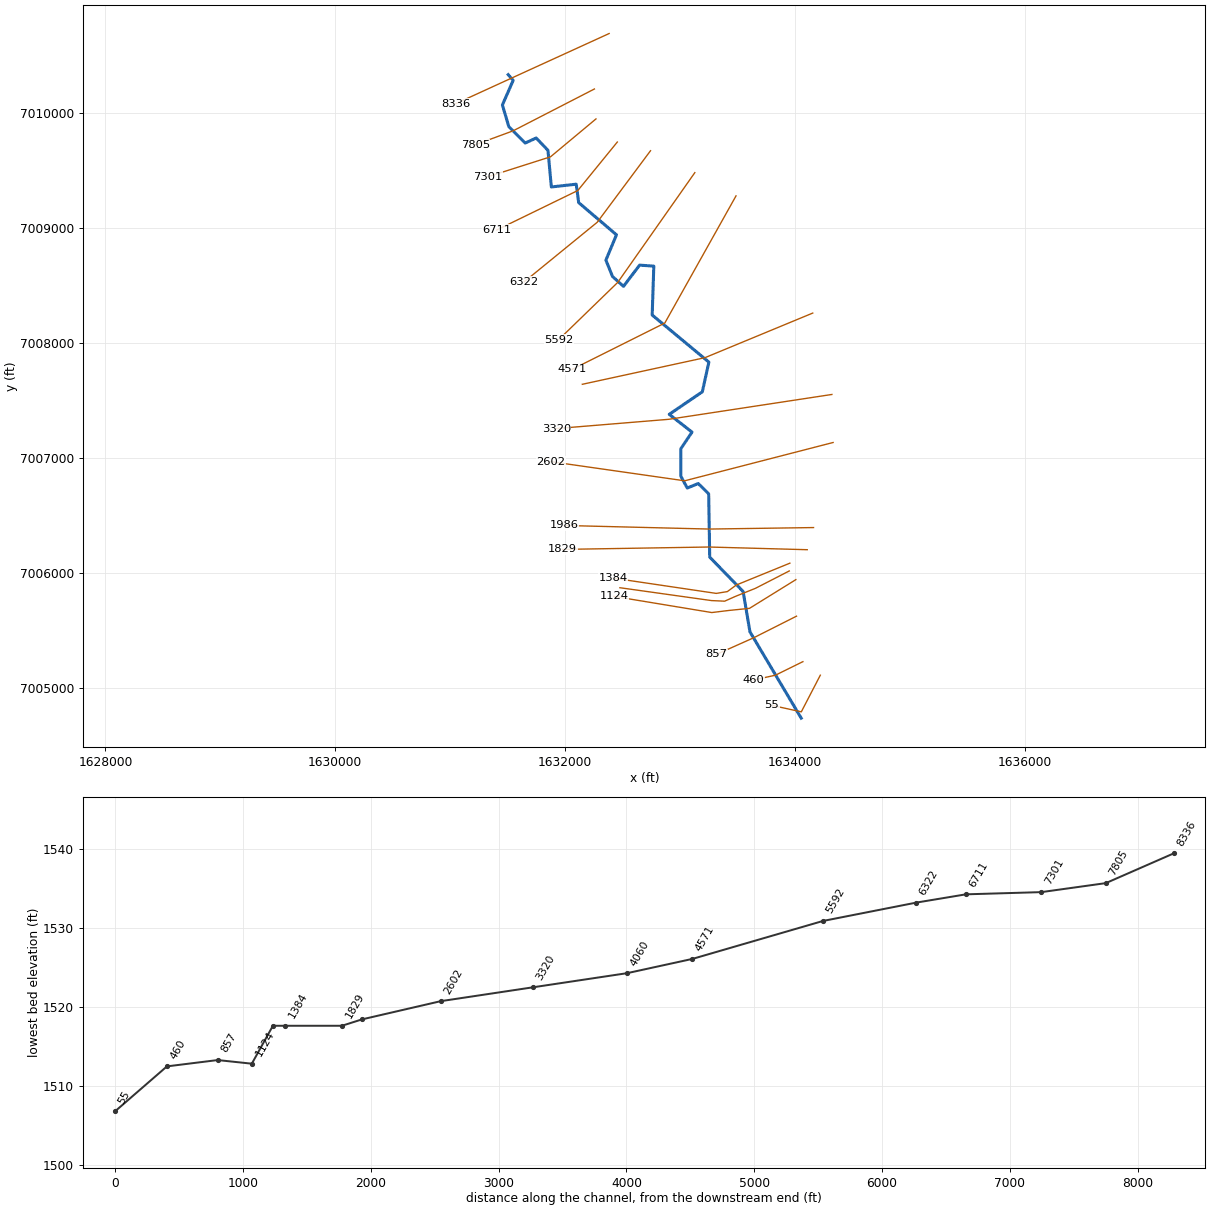
--- Chimney Creek 1153.prj (project) ---

Proj Title=Chimney Creek 1153 Base Level Engineering
Current Plan=p01
Default Exp/Contr=0.3,0.1
English Units
Geom File=g01
Flow File=f01
Plan File=p01
BEGIN DESCRIPTION:
Chimney Creek 1153
END DESCRIPTION:

--- Chimney Creek 1153.p01 (plan) ---

Plan Title=Multiple Run
Short Identifier=Multiple
Geom File=g01
Flow File=f01
Subcritical Flow
K Sum by GR= 0
Std Step Tol= 0.01
Critical Tol= 0.01
Num of Std Step Trials= 20
Max Error Tol= 0.3
Flow Tol Ratio= 0.001
Split Flow NTrial= 30
Split Flow Tol= 0.02
Split Flow Ratio= 0.02
Log Output Level= 0
Friction Slope Method= 1
Unsteady Friction Slope Method= 2
Unsteady Bridges Friction Slope Method= 1
Parabolic Critical Depth
Global Vel Dist=  1 , 1 , 1
Global Log Level= 0
CheckData=True
Encroach Param= -1, 0, 0, 0
BEGIN DESCRIPTION:
Multiple Run
END DESCRIPTION:

--- Chimney Creek 1153.f01 (steady flow) ---

Flow Title=Multiple
Number of Profiles=7
Profile Names=10-year,25-year,50-year,1pct_min,100-year,1pct_plu,500-year
River Rch & RM= Chimney Creek 11,Reach-1,8336
     241     333     408     250     498     995     752
River Rch & RM= Chimney Creek 11,Reach-1,6711
     336     470     581     357     713    1423    1088
Boundary for River Rch & Prof#=Chimney Creek 11,Reach-1,1
Up Type=0
Dn Type=3
Dn Slope=0.005
Boundary for River Rch & Prof#=Chimney Creek 11,Reach-1,2
Up Type=0
Dn Type=3
Dn Slope=0.005
Boundary for River Rch & Prof#=Chimney Creek 11,Reach-1,3
Up Type=0
Dn Type=3
Dn Slope=0.005
Boundary for River Rch & Prof#=Chimney Creek 11,Reach-1,4
Up Type=0
Dn Type=3
Dn Slope=0.005
Boundary for River Rch & Prof#=Chimney Creek 11,Reach-1,5
Up Type=0
Dn Type=3
Dn Slope=0.005
Boundary for River Rch & Prof#=Chimney Creek 11,Reach-1,6
Up Type=0
Dn Type=3
Dn Slope=0.005
Boundary for River Rch & Prof#=Chimney Creek 11,Reach-1,7
Up Type=0
Dn Type=3
Dn Slope=0.005

--- Chimney Creek 1153.g01 (geometry) ---

Geom Title=Existing Conditions

River Reach=Chimney Creek 11,Reach-1
Reach XY= 30
      1631505.00      7010338.00      1631548.41      7010288.01
      1631454.52      7010074.20      1631510.52      7009885.57
      1631653.02      7009743.00      1631748.78      7009786.53
      1631851.16      7009679.38      1631880.59      7009360.69
      1632097.00      7009384.86      1632118.50      7009224.32
      1632447.33      7008944.39      1632355.15      7008723.59
      1632412.88      7008581.84      1632508.34      7008495.58
      1632648.55      7008680.36      1632772.22      7008671.79
      1632758.07      7008246.30      1633251.34      7007836.44
      1633194.48      7007578.21      1632906.48      7007382.11
      1633104.52      7007227.53      1633007.18      7007082.55
      1633007.34      7006843.49      1633063.47      7006740.66
      1633158.40      7006780.18      1633249.54      7006690.48
      1633258.75      7006139.55      1633549.46      7005840.37
      1633608.75      7005489.55      1634055.00      7004738.00

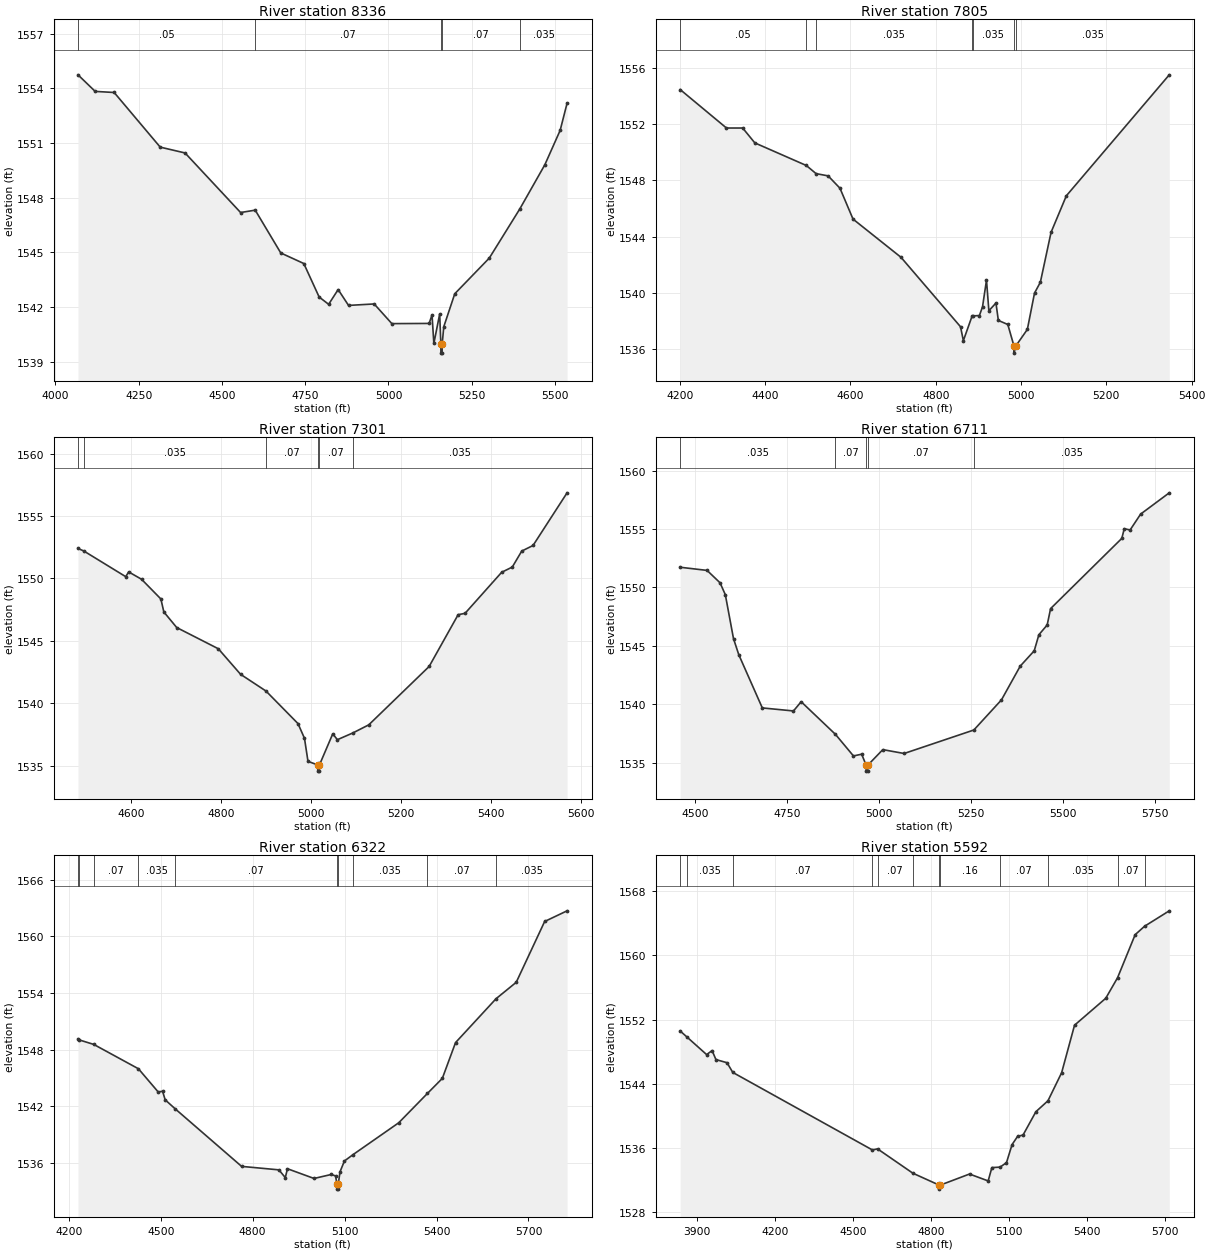
Type RM Length L Ch R = 1,8336,531,531,531
BEGIN DESCRIPTION:
Chimney Creek 1153 17.0
END DESCRIPTION:
XS GIS Cut Line= 3
      1632383.70      7010695.92      1631535.95      7010308.69
      1631048.50      7010085.54
#Sta/Elev= 30
  4068.0 1554.74  4119.6 1553.83  4176.6 1553.77  4314.8 1550.77  4389.4 1550.45
  4556.1 1547.18  4600.0 1547.31  4676.7 1544.96  4745.8 1544.38  4791.9 1542.54
  4820.4 1542.14  4848.9 1542.95  4880.1 1542.08  4957.1 1542.16  5010.1 1541.08
  5122.0 1541.09  5130.7 1541.56  5136.2 1539.99  5153.7 1541.61  5157.2 1539.96
  5157.4 1539.46  5160.9 1539.46  5161.2 1539.96  5166.0 1540.91  5199.0 1542.72
  5302.7 1544.68  5394.3 1547.38  5469.3 1549.80  5515.3 1551.69  5536.1 1553.18
#Mann=5,-1,0
  4068.0    0.05       0  4600.0    0.07       0  5157.2    0.07       0
  5161.2    0.07       0  5394.3   0.035       0
Bank Sta=5157.2,5161.2
Exp/Cntr=0.3,0.1

Type RM Length L Ch R = 1,7805,504,504,504
BEGIN DESCRIPTION:
Mapping XS 9e33bfc2
END DESCRIPTION:
XS GIS Cut Line= 3
      1632255.26      7010213.29      1631546.92      7009848.71
      1631218.56      7009727.73
#Sta/Elev= 30
  4200.9 1554.47  4309.4 1551.73  4347.4 1551.73  4375.9 1550.67  4496.6 1549.06
  4519.5 1548.48  4547.7 1548.32  4575.5 1547.44  4606.1 1545.24  4718.5 1542.52
  4858.1 1537.57  4864.8 1536.58  4885.0 1538.31  4886.7 1538.34  4902.4 1538.37
  4909.7 1538.99  4919.0 1540.89  4924.6 1538.71  4941.2 1539.26  4946.8 1538.02
  4969.0 1537.73  4983.5 1536.19  4983.8 1535.69  4987.5 1536.19  5014.8 1537.38
  5031.6 1539.97  5045.3 1540.74  5070.4 1544.30  5106.2 1546.90  5347.5 1555.52
#Mann=7,-1,0
  4200.9    0.05       0  4496.6    0.07       0  4519.5   0.035       0
  4885.0    0.07       0  4886.7   0.035       0  4983.5   0.035       0
  4987.5   0.035       0
Bank Sta=4983.5,4987.5
Exp/Cntr=0.3,0.1

Type RM Length L Ch R = 1,7301,590,590,590
BEGIN DESCRIPTION:
Mapping XS a77037b1
END DESCRIPTION:
XS GIS Cut Line= 3
      1632269.11      7009952.85      1631873.31      7009623.01
      1631329.06      7009449.69
#Sta/Elev= 30
  4482.9 1552.40  4495.7 1552.20  4588.9 1550.14  4595.5 1550.52  4624.1 1549.93
  4667.0 1548.35  4673.6 1547.31  4702.2 1546.06  4794.6 1544.36  4844.1 1542.31
  4900.5 1540.97  4971.6 1538.36  4986.0 1537.18  4993.8 1535.33  5015.3 1535.05
  5015.6 1534.55  5019.1 1534.55  5019.3 1535.05  5048.8 1537.54  5059.1 1537.07
  5093.4 1537.61  5128.8 1538.26  5262.9 1542.94  5327.3 1547.09  5342.7 1547.20
  5424.0 1550.49  5447.6 1550.91  5468.6 1552.19  5493.7 1552.64  5569.3 1556.86
#Mann=6,-1,0
  4482.9    0.05       0  4495.7   0.035       0  4900.5    0.07       0
  5015.3    0.07       0  5019.3    0.07       0  5093.4   0.035       0
Bank Sta=5015.3,5019.3
Exp/Cntr=0.3,0.1

Type RM Length L Ch R = 1,6711,389,389,389
BEGIN DESCRIPTION:
Mapping XS 7704c8fd
END DESCRIPTION:
XS GIS Cut Line= 3
      1632454.57      7009751.67      1632110.81      7009329.78
      1631405.08      7008986.04
#Sta/Elev= 30
  4460.0 1551.72  4533.1 1551.45  4568.3 1550.39  4582.7 1549.37  4604.9 1545.61
  4619.3 1544.23  4683.2 1539.68  4767.9 1539.42  4788.8 1540.21  4881.9 1537.42
  4930.9 1535.57  4953.2 1535.72  4965.5 1534.77  4965.8 1534.27  4969.4 1534.27
  4969.6 1534.77  5010.7 1536.11  5068.6 1535.78  5258.1 1537.79  5333.2 1540.37
  5384.2 1543.26  5422.2 1544.57  5434.8 1545.94  5457.4 1546.78  5466.7 1548.18
  5660.2 1554.19  5666.9 1555.02  5682.8 1554.91  5711.4 1556.27  5789.2 1558.09
#Mann=5,-1,0
  4460.0   0.035       0  4881.9    0.07       0  4965.5    0.07       0
  4969.6    0.07       0  5258.1   0.035       0
Bank Sta=4965.5,4969.6
Exp/Cntr=0.3,0.1

Type RM Length L Ch R = 1,6322,730,730,730
BEGIN DESCRIPTION:
Mapping XS a8ae4763
END DESCRIPTION:
XS GIS Cut Line= 3
      1632743.65      7009676.17      1632280.08      7009053.74
      1631644.69      7008535.54
#Sta/Elev= 30
  4230.0 1549.14  4232.6 1549.04  4281.4 1548.55  4427.2 1545.97  4491.5 1543.52
  4506.1 1543.58  4514.5 1542.68  4547.0 1541.73  4763.9 1535.63  4885.7 1535.26
  4906.5 1534.44  4913.5 1535.38  5000.3 1534.35  5056.3 1534.77  5070.6 1534.62
  5075.1 1533.72  5075.4 1533.22  5079.0 1533.22  5079.2 1533.72  5085.0 1535.05
  5099.4 1536.20  5127.3 1536.87  5276.7 1540.25  5370.4 1543.36  5418.9 1544.95
  5462.0 1548.74  5594.2 1553.39  5660.1 1555.13  5752.8 1561.57  5826.0 1562.70
#Mann=10,-1,0
  4230.0    0.07       0  4232.6   0.035       0  4281.4    0.07       0
  4427.2   0.035       0  4547.0    0.07       0  5075.1    0.07       0
  5079.2    0.07       0  5127.3   0.035       0  5370.4    0.07       0
  5594.2   0.035       0
Bank Sta=5075.1,5079.2
Exp/Cntr=0.3,0.1

Type RM Length L Ch R = 1,5592,1021,1021,1021
BEGIN DESCRIPTION:
Mapping XS 6eaddd87
END DESCRIPTION:
XS GIS Cut Line= 3
      1633129.16      7009485.44      1632458.57      7008530.56
      1631945.06      7008032.22
#Sta/Elev= 30
  3835.3 1550.58  3860.3 1549.86  3937.1 1547.64  3958.1 1548.14  3972.9 1547.02
  4015.5 1546.63  4037.8 1545.42  4574.9 1535.77  4595.0 1535.90  4731.0 1532.87
  4832.1 1531.39  4832.3 1530.89  4836.3 1531.39  4948.9 1532.77  5020.7 1531.91
  5034.9 1533.57  5066.6 1533.63  5091.2 1534.19  5112.6 1536.43  5133.7 1537.45
  5155.0 1537.63  5204.4 1540.53  5250.8 1541.89  5303.4 1545.38  5353.1 1551.30
  5473.2 1554.65  5518.7 1557.21  5586.4 1562.57  5622.7 1563.62  5717.7 1565.54
#Mann=12,-1,0
  3835.3    0.07       0  3860.3   0.035       0  4037.8    0.07       0
  4574.9   0.035       0  4595.0    0.07       0  4731.0    0.16       0
  4832.1    0.07       0  4836.3    0.16       0  5066.6    0.07       0
  5250.8   0.035       0  5518.7    0.07       0  5622.7   0.035       0
Bank Sta=4832.1,4836.3
Exp/Cntr=0.3,0.1

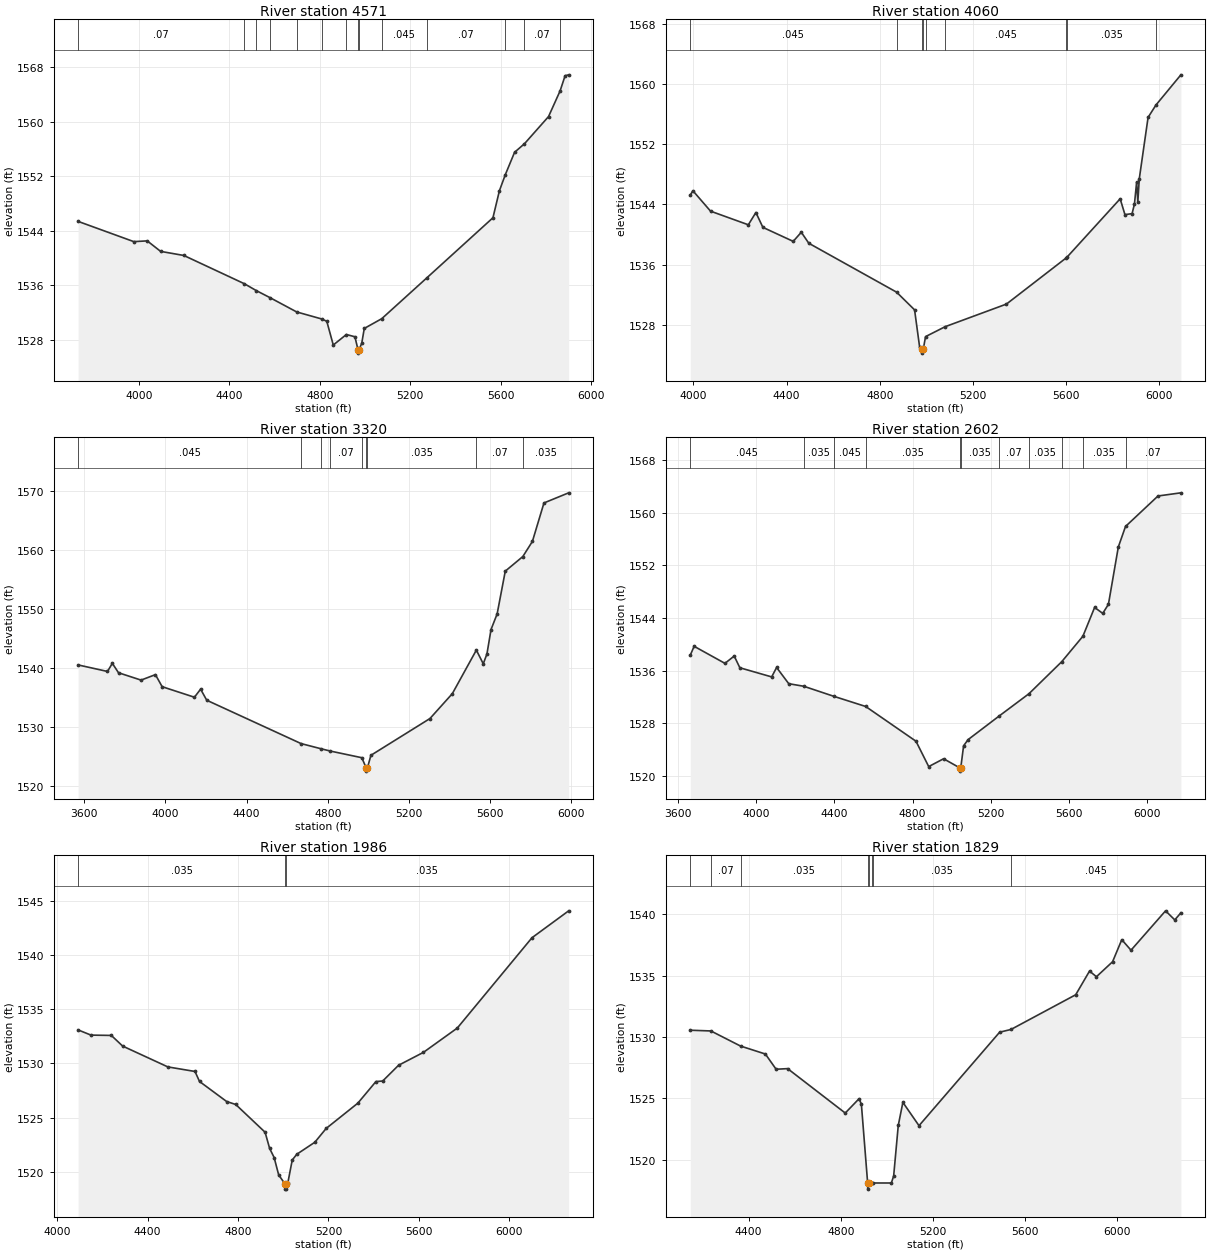
Type RM Length L Ch R = 1,4571,511,511,511
BEGIN DESCRIPTION:
Mapping XS 6f4edb5a
END DESCRIPTION:
XS GIS Cut Line= 3
      1633487.68      7009283.20      1632867.86      7008176.39
      1632060.86      7007772.89
#Sta/Elev= 30
  3730.7 1545.40  3977.3 1542.43  4036.7 1542.54  4096.0 1541.00  4198.8 1540.40
  4466.9 1536.25  4518.7 1535.26  4580.8 1534.20  4697.9 1532.12  4808.5 1531.09
  4831.2 1530.75  4859.9 1527.27  4917.9 1528.81  4955.6 1528.48  4969.4 1526.58
  4969.7 1526.08  4973.7 1526.58  4985.9 1527.53  4997.1 1529.70  5074.4 1531.13
  5273.6 1537.11  5566.4 1545.93  5595.0 1549.89  5620.8 1552.22  5662.1 1555.53
  5706.0 1556.79  5812.4 1560.77  5863.6 1564.54  5885.7 1566.76  5901.5 1566.89
#Mann=14,-1,0
  3730.7    0.07       0  4466.9   0.035       0  4518.7    0.07       0
  4580.8   0.035       0  4697.9    0.07       0  4808.5    0.16       0
  4917.9   0.035       0  4969.4   0.035       0  4973.7   0.035       0
  5074.4   0.045       0  5273.6    0.07       0  5620.8   0.035       0
  5706.0    0.07       0  5863.6   0.035       0
Bank Sta=4969.4,4973.7
Exp/Cntr=0.3,0.1

Type RM Length L Ch R = 1,4060,740,740,740
BEGIN DESCRIPTION:
Mapping XS 1a3c26a0
END DESCRIPTION:
XS GIS Cut Line= 3
      1634155.38      7008263.38      1633217.86      7007875.35
      1632150.17      7007643.58
#Sta/Elev= 30
  3986.3 1545.24  3997.5 1545.82  4073.3 1543.11  4235.6 1541.30  4268.1 1542.93
  4298.1 1540.96  4428.4 1539.10  4463.1 1540.31  4495.4 1538.85  4872.4 1532.36
  4949.7 1530.01  4971.6 1525.02  4981.8 1524.77  4982.2 1524.27  4986.9 1524.77
  4996.8 1526.46  5081.1 1527.78  5344.3 1530.78  5601.5 1536.92  5604.5 1537.01
  5832.7 1544.75  5853.2 1542.65  5883.9 1542.78  5894.1 1544.06  5903.5 1546.99
  5908.6 1544.31  5914.6 1547.36  5952.6 1555.55  5986.3 1557.19  6093.5 1561.20
#Mann=9,-1,0
  3986.3   0.045       0  4872.4    0.07       0  4981.8   0.035       0
  4986.9    0.07       0  4996.8   0.035       0  5081.1   0.045       0
  5601.5    0.07       0  5604.5   0.035       0  5986.3    0.07       0
Bank Sta=4981.8,4986.9
Exp/Cntr=0.3,0.1

Type RM Length L Ch R = 1,3320,718,718,718
BEGIN DESCRIPTION:
Mapping XS 4ec9df10
END DESCRIPTION:
XS GIS Cut Line= 3
      1634322.00      7007555.03      1632902.76      7007338.89
      1631923.58      7007258.16
#Sta/Elev= 30
  3569.6 1540.52  3714.6 1539.41  3738.5 1540.79  3768.9 1539.19  3880.1 1537.94
  3950.9 1538.87  3984.0 1536.82  4143.1 1535.03  4173.5 1536.40  4203.8 1534.52
  4668.8 1527.15  4768.6 1526.26  4812.9 1525.88  4968.1 1524.75  4990.2 1522.97
  4990.6 1522.47  4995.4 1522.97  5013.0 1525.16  5304.0 1531.41  5414.3 1535.64
  5532.6 1543.04  5566.8 1540.71  5584.9 1542.40  5605.0 1546.54  5635.1 1549.19
  5675.2 1556.46  5761.7 1558.94  5808.9 1561.51  5865.9 1568.05  5987.7 1569.77
#Mann=9,-1,0
  3569.6   0.045       0  4668.8    0.07       0  4768.6   0.035       0
  4812.9    0.07       0  4968.1   0.035       0  4990.2   0.035       0
  4995.4   0.035       0  5532.6    0.07       0  5761.7   0.035       0
Bank Sta=4990.2,4995.4
Exp/Cntr=0.3,0.1

Type RM Length L Ch R = 1,2602,616,616,616
BEGIN DESCRIPTION:
Mapping XS d1740a22
END DESCRIPTION:
XS GIS Cut Line= 3
      1634332.43      7007137.08      1633040.74      7006803.74
      1631878.31      7006970.17
#Sta/Elev= 30
  3663.1 1538.33  3682.8 1539.68  3840.3 1537.09  3887.7 1538.20  3916.5 1536.42
  4079.2 1535.03  4104.5 1536.46  4166.5 1534.00  4243.3 1533.61  4397.4 1532.08
  4559.8 1530.54  4817.1 1525.26  4882.1 1521.41  4958.3 1522.60  5040.7 1521.22
  5041.1 1520.72  5046.0 1521.22  5060.5 1524.57  5083.7 1525.51  5243.5 1529.12
  5394.8 1532.48  5562.2 1537.34  5670.5 1541.21  5730.3 1545.58  5771.9 1544.68
  5801.0 1546.06  5851.5 1554.76  5888.3 1557.88  6054.4 1562.51  6171.4 1562.99
#Mann=11,-1,0
  3663.1   0.045       0  4243.3   0.035       0  4397.4   0.045       0
  4559.8   0.035       0  5040.7   0.035       0  5046.0   0.035       0
  5243.5    0.07       0  5394.8   0.035       0  5562.2    0.07       0
  5670.5   0.035       0  5888.3    0.07       0
Bank Sta=5040.7,5046
Exp/Cntr=0.3,0.1

Type RM Length L Ch R = 1,1986,157,157,157
BEGIN DESCRIPTION:
Mapping XS 0f696f03
END DESCRIPTION:
XS GIS Cut Line= 3
      1634162.09      7006396.84      1633255.80      7006383.81
      1631992.77      7006415.06
#Sta/Elev= 30
  4092.8 1533.08  4149.9 1532.60  4239.9 1532.57  4289.9 1531.59  4489.9 1529.67
  4609.9 1529.25  4629.9 1528.33  4750.0 1526.48  4790.0 1526.21  4920.0 1523.65
  4940.0 1522.16  4960.0 1521.32  4980.0 1519.72  5007.3 1518.91  5007.7 1518.41
  5012.2 1518.41  5012.7 1518.91  5020.0 1518.93  5040.0 1521.09  5060.0 1521.62
  5140.0 1522.73  5190.0 1524.00  5330.1 1526.33  5410.1 1528.32  5440.1 1528.37
  5510.1 1529.82  5620.2 1531.01  5770.0 1533.25  6100.3 1541.57  6262.6 1544.05
#Mann=3,-1,0
  4092.8   0.035       0  5007.3   0.035       0  5012.7   0.035       0
Bank Sta=5007.3,5012.7
Exp/Cntr=0.3,0.1

Type RM Length L Ch R = 1,1829,445,445,445
BEGIN DESCRIPTION:
Mapping XS 85d9d2fa
END DESCRIPTION:
XS GIS Cut Line= 3
      1634107.36      7006204.13      1633250.59      7006227.56
      1631978.55      7006206.75
#Sta/Elev= 30
  4147.2 1530.55  4236.7 1530.49  4365.3 1529.26  4473.2 1528.61  4519.7 1527.37
  4569.7 1527.42  4819.8 1523.80  4879.8 1524.97  4889.8 1524.52  4917.0 1518.10
  4917.5 1517.60  4922.6 1518.10  4937.0 1518.10  4938.1 1518.10  5019.9 1518.10
  5029.9 1518.67  5049.9 1522.79  5069.9 1524.67  5139.9 1522.77  5489.9 1530.39
  5538.9 1530.61  5820.0 1533.44  5880.0 1535.37  5910.0 1534.91  5980.0 1536.13
  6020.0 1537.93  6060.0 1537.07  6210.0 1540.28  6250.0 1539.54  6276.5 1540.12
#Mann=8,-1,0
  4147.2   0.035       0  4236.7    0.07       0  4365.3   0.035       0
  4917.0   0.035       0  4922.6   0.035       0  4937.0   0.033       0
  4938.1   0.035       0  5538.9   0.045       0
Bank Sta=4917,4922.6
Exp/Cntr=0.3,0.1

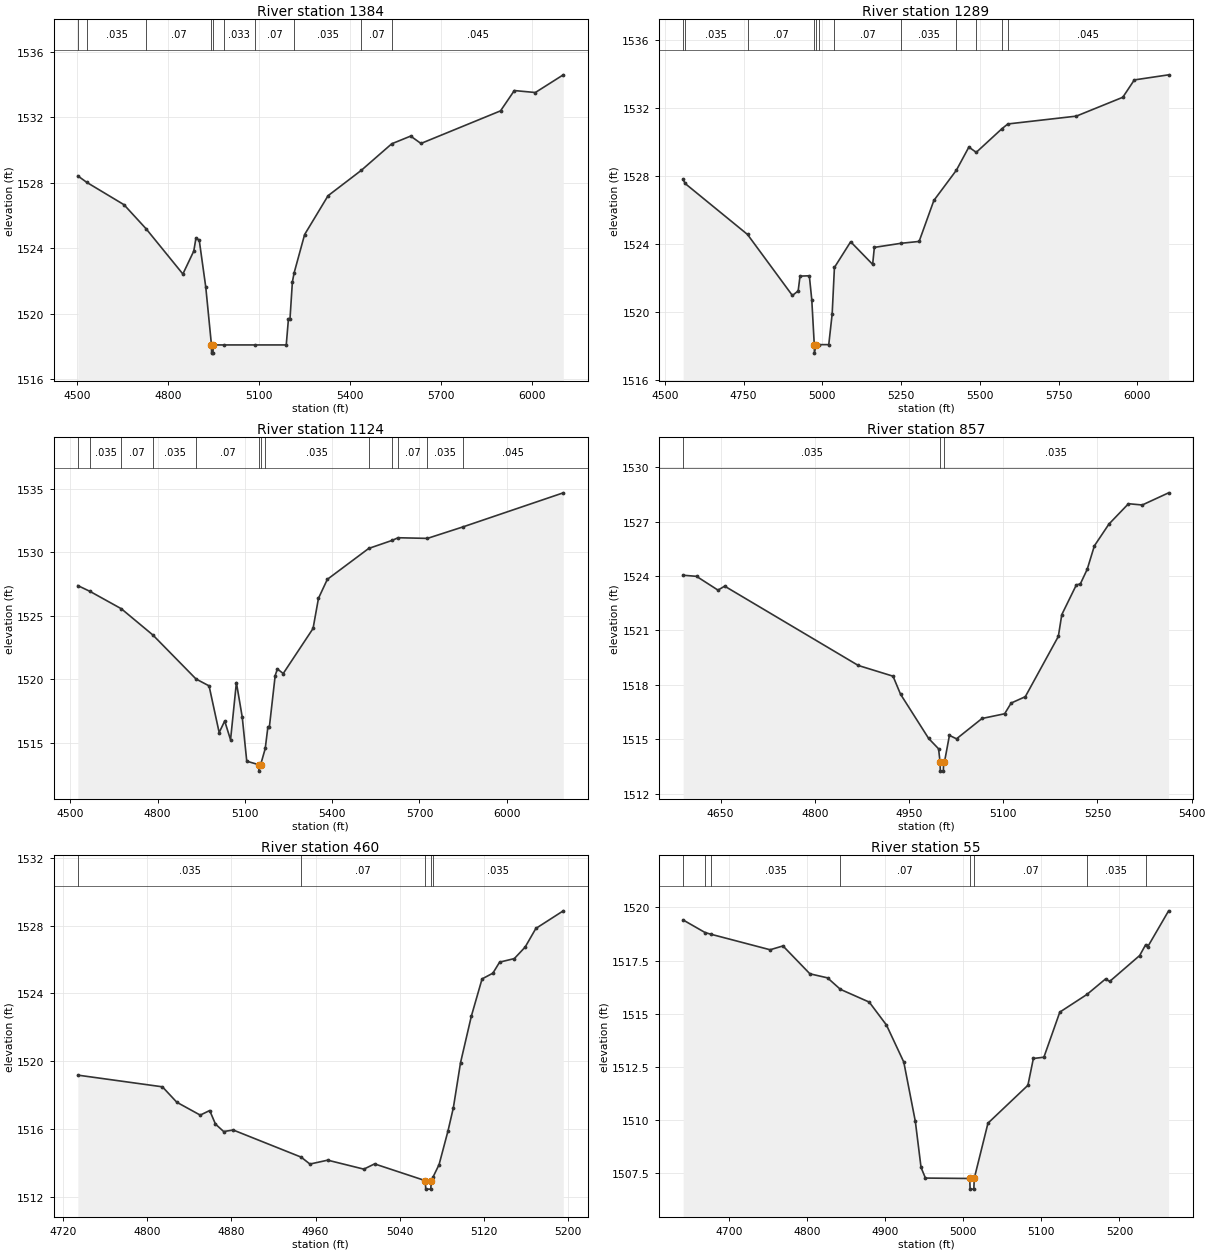
Type RM Length L Ch R = 1,1384,95,95,95
BEGIN DESCRIPTION:
Mapping XS defb4db3
END DESCRIPTION:
XS GIS Cut Line= 5
      1633956.28      7006086.93      1633490.17      7005896.83
      1633412.05      7005839.54      1633315.69      7005823.92
      1632419.96      7005956.72
#Sta/Elev= 30
  4501.4 1528.42  4531.4 1528.02  4654.0 1526.66  4727.0 1525.19  4848.4 1522.43
  4884.4 1523.83  4891.6 1524.62  4902.4 1524.50  4924.0 1521.63  4942.8 1518.10
  4943.2 1517.60  4947.9 1517.60  4948.4 1518.10  4982.6 1518.10  5086.6 1518.10
  5189.8 1518.10  5197.1 1519.70  5202.2 1519.70  5210.1 1521.95  5215.7 1522.49
  5250.5 1524.84  5327.9 1527.21  5437.7 1528.76  5538.2 1530.38  5600.7 1530.85
  5634.7 1530.40  5897.5 1532.39  5943.1 1533.63  6012.5 1533.51  6104.8 1534.59
#Mann=10,-1,0
  4501.4    0.07       0  4531.4   0.035       0  4727.0    0.07       0
  4942.8   0.033       0  4948.4    0.07       0  4982.6   0.033       0
  5086.6    0.07       0  5215.7   0.035       0  5437.7    0.07       0
  5538.2   0.045       0
Bank Sta=4942.8,4948.4
Exp/Cntr=0.3,0.1

Type RM Length L Ch R = 1,1289,165,165,165
BEGIN DESCRIPTION:
Mapping XS 08bf2e4f
END DESCRIPTION:
XS GIS Cut Line= 6
      1633951.15      7006019.25      1633656.84      7005868.19
      1633482.36      7005797.88      1633388.61      7005756.21
      1633274.03      7005761.42      1632477.18      7005873.39
#Sta/Elev= 30
  4558.2 1527.82  4564.3 1527.58  4762.5 1524.58  4905.0 1520.99  4923.3 1521.26
  4929.2 1522.13  4958.7 1522.15  4966.5 1520.74  4974.4 1518.10  4974.9 1517.60
  4980.0 1518.10  4989.5 1518.10  5020.4 1518.10  5031.2 1519.90  5038.4 1522.64
  5089.9 1524.15  5159.7 1522.82  5165.1 1523.82  5249.5 1524.06  5307.2 1524.17
  5354.0 1526.58  5425.5 1528.36  5465.1 1529.72  5488.5 1529.41  5570.0 1530.80
  5588.9 1531.08  5806.1 1531.54  5953.7 1532.65  5990.2 1533.67  6099.1 1533.97
#Mann=12,-1,0
  4558.2    0.07       0  4564.3   0.035       0  4762.5    0.07       0
  4974.4   0.033       0  4980.0    0.07       0  4989.5   0.033       0
  5038.4    0.07       0  5249.5   0.035       0  5425.5    0.07       0
  5488.5   0.035       0  5570.0    0.07       0  5588.9   0.045       0
Bank Sta=4974.4,4980
Exp/Cntr=0.3,0.1

Type RM Length L Ch R = 1,1124,267,267,267
BEGIN DESCRIPTION:
Mapping XS 1803a367
END DESCRIPTION:
XS GIS Cut Line= 5
      1634008.40      7005943.71      1633604.75      7005693.71
      1633425.07      7005675.48      1633276.63      7005657.25
      1632425.02      7005797.88
#Sta/Elev= 30
  4526.1 1527.37  4567.5 1526.92  4675.6 1525.55  4783.9 1523.49  4932.3 1520.03
  4977.1 1519.49  5011.8 1515.82  5030.8 1516.73  5050.9 1515.25  5071.0 1519.75
  5091.1 1517.03  5106.6 1513.57  5148.6 1513.29  5149.0 1512.79  5154.3 1513.29
  5170.1 1514.57  5179.0 1516.22  5184.1 1516.22  5204.3 1520.30  5211.8 1520.82
  5231.9 1520.46  5334.4 1524.00  5353.0 1526.37  5383.4 1527.86  5525.7 1530.29
  5605.9 1530.92  5626.5 1531.13  5727.4 1531.08  5849.1 1531.98  6194.2 1534.66
#Mann=13,-1,0
  4526.1    0.07       0  4567.5   0.035       0  4675.6    0.07       0
  4783.9   0.035       0  4932.3    0.07       0  5148.6    0.07       0
  5154.3    0.07       0  5170.1   0.035       0  5525.7    0.07       0
  5605.9   0.035       0  5626.5    0.07       0  5727.4   0.035       0
  5849.1   0.045       0
Bank Sta=5148.6,5154.3
Exp/Cntr=0.3,0.1

Type RM Length L Ch R = 1,857,397,397,397
BEGIN DESCRIPTION:
Mapping XS e2fe53b6
END DESCRIPTION:
XS GIS Cut Line= 3
      1634013.97      7005625.79      1633642.46      7005438.30
      1633316.65      7005292.72
#Sta/Elev= 30
  4590.3 1524.04  4611.6 1523.98  4645.8 1523.22  4656.4 1523.44  4869.2 1519.07
  4924.5 1518.48  4936.4 1517.49  4981.2 1515.05  4997.0 1514.48  4999.4 1513.75
  4999.8 1513.25  5004.6 1513.25  5005.1 1513.75  5006.4 1513.75  5014.3 1515.22
  5025.6 1515.03  5066.2 1516.15  5102.2 1516.41  5112.6 1517.00  5135.1 1517.35
  5187.7 1520.67  5193.2 1521.87  5216.4 1523.51  5222.7 1523.56  5233.7 1524.37
  5245.1 1525.66  5268.3 1526.86  5299.4 1527.98  5321.3 1527.91  5363.3 1528.58
#Mann=3,-1,0
  4590.3   0.035       0  4999.4   0.035       0  5005.1   0.035       0
Bank Sta=4999.4,5005.1
Exp/Cntr=0.3,0.1

Type RM Length L Ch R = 1,460,405,405,405
BEGIN DESCRIPTION:
Mapping XS 9497b515
END DESCRIPTION:
XS GIS Cut Line= 3
      1634069.51      7005229.95      1633829.96      7005111.91
      1633639.49      7005070.35
#Sta/Elev= 30
  4733.8 1519.18  4814.3 1518.49  4828.0 1517.58  4850.3 1516.82  4859.3 1517.09
  4864.8 1516.29  4872.6 1515.85  4881.7 1515.94  4946.3 1514.34  4954.7 1513.93
  4971.6 1514.16  5006.0 1513.63  5016.2 1513.94  5064.5 1512.95  5064.9 1512.45
  5069.7 1512.45  5070.2 1512.95  5071.9 1513.17  5077.6 1513.90  5086.1 1515.89
  5091.2 1517.26  5098.0 1519.91  5108.3 1522.66  5118.5 1524.86  5128.8 1525.20
  5135.2 1525.85  5149.2 1526.06  5159.5 1526.74  5169.7 1527.84  5195.8 1528.88
#Mann=5,-1,0
  4733.8   0.035       0  4946.3    0.07       0  5064.5    0.07       0
  5070.2    0.07       0  5071.9   0.035       0
Bank Sta=5064.5,5070.2
Exp/Cntr=0.3,0.1

Type RM Length L Ch R = 1,55,0,0,0
BEGIN DESCRIPTION:
Chimney Creek 1153 1.0
END DESCRIPTION:
XS GIS Cut Line= 3
      1634221.17      7005112.28      1634055.76      7004793.31
      1633798.80      7004849.84
#Sta/Elev= 30
  4640.7 1519.41  4668.8 1518.82  4676.3 1518.74  4752.2 1518.01  4768.7 1518.19
  4803.2 1516.88  4825.8 1516.69  4842.3 1516.15  4879.3 1515.55  4901.4 1514.47
  4923.6 1512.73  4938.4 1509.94  4945.7 1507.78  4951.3 1507.28  5008.1 1507.26
  5008.6 1506.76  5013.4 1506.76  5013.9 1507.26  5031.5 1509.86  5082.7 1511.64
  5089.7 1512.90  5103.2 1512.96  5123.6 1515.08  5158.4 1515.91  5182.3 1516.64
  5187.5 1516.52  5226.0 1517.74  5233.7 1518.25  5236.3 1518.15  5263.1 1519.84
#Mann=8,-1,0
  4640.7   0.035       0  4668.8    0.07       0  4676.3   0.035       0
  4842.3    0.07       0  5008.1    0.07       0  5013.9    0.07       0
  5158.4   0.035       0  5233.7    0.07       0
Bank Sta=5008.1,5013.9
Exp/Cntr=0.3,0.1

Chan Stop Cuts=-1