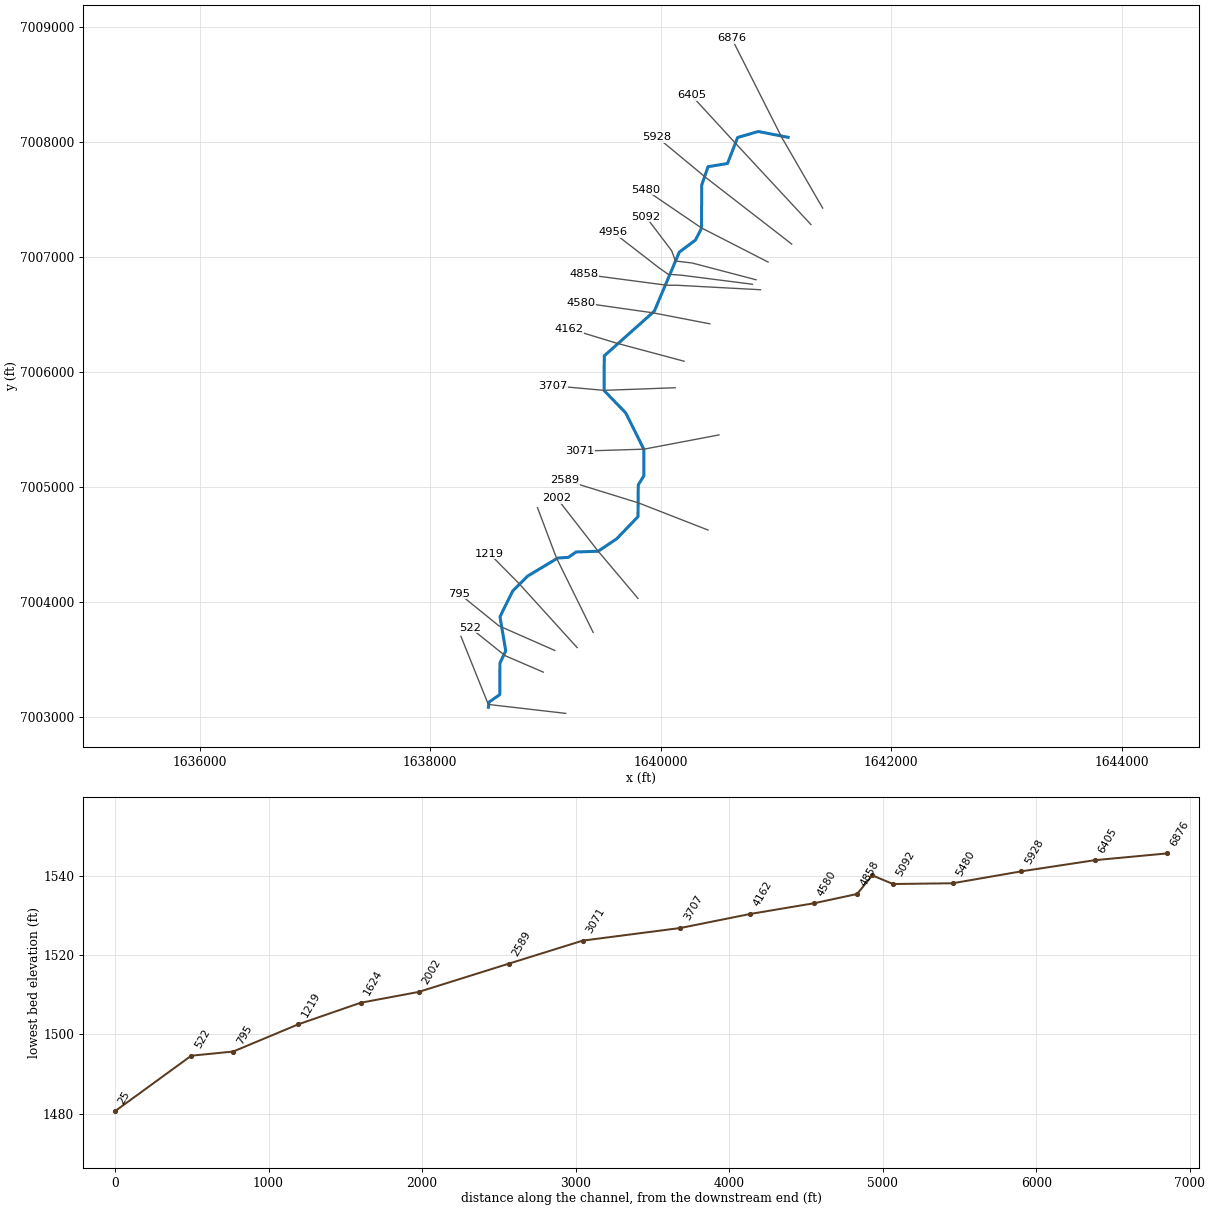
--- Chimney Creek 1154.prj (project) ---

Proj Title=Chimney Creek 1154 Base Level Engineering
Current Plan=p01
Default Exp/Contr=0.3,0.1
English Units
Geom File=g01
Flow File=f01
Plan File=p01
BEGIN DESCRIPTION:
Chimney Creek 1154
END DESCRIPTION:

--- Chimney Creek 1154.p01 (plan) ---

Plan Title=Multiple Run
Short Identifier=Multiple
Geom File=g01
Flow File=f01
Subcritical Flow
K Sum by GR= 0
Std Step Tol= 0.01
Critical Tol= 0.01
Num of Std Step Trials= 20
Max Error Tol= 0.3
Flow Tol Ratio= 0.001
Split Flow NTrial= 30
Split Flow Tol= 0.02
Split Flow Ratio= 0.02
Log Output Level= 0
Friction Slope Method= 1
Unsteady Friction Slope Method= 2
Unsteady Bridges Friction Slope Method= 1
Parabolic Critical Depth
Global Vel Dist=  1 , 1 , 1
Global Log Level= 0
CheckData=True
Encroach Param= -1, 0, 0, 0
BEGIN DESCRIPTION:
Multiple Run
END DESCRIPTION:

--- Chimney Creek 1154.f01 (steady flow) ---

Flow Title=Multiple
Number of Profiles=7
Profile Names=10-year,25-year,50-year,1pct_min,100-year,1pct_plu,500-year
River Rch & RM= Chimney Creek 11,Reach-1,6876
     194     264     320     194     387     772     572
River Rch & RM= Chimney Creek 11,Reach-1,6405
     390     552     689     427     853    1701    1324
Boundary for River Rch & Prof#=Chimney Creek 11,Reach-1,1
Up Type=0
Dn Type=3
Dn Slope=0.005
Boundary for River Rch & Prof#=Chimney Creek 11,Reach-1,2
Up Type=0
Dn Type=3
Dn Slope=0.005
Boundary for River Rch & Prof#=Chimney Creek 11,Reach-1,3
Up Type=0
Dn Type=3
Dn Slope=0.005
Boundary for River Rch & Prof#=Chimney Creek 11,Reach-1,4
Up Type=0
Dn Type=3
Dn Slope=0.005
Boundary for River Rch & Prof#=Chimney Creek 11,Reach-1,5
Up Type=0
Dn Type=3
Dn Slope=0.005
Boundary for River Rch & Prof#=Chimney Creek 11,Reach-1,6
Up Type=0
Dn Type=3
Dn Slope=0.005
Boundary for River Rch & Prof#=Chimney Creek 11,Reach-1,7
Up Type=0
Dn Type=3
Dn Slope=0.005

--- Chimney Creek 1154.g01 (geometry) ---

Geom Title=Existing Conditions

River Reach=Chimney Creek 11,Reach-1
Reach XY= 30
      1641105.00      7008038.00      1640845.74      7008088.50
      1640666.85      7008036.27      1640579.01      7007810.66
      1640410.08      7007782.96      1640355.52      7007622.79
      1640353.81      7007248.48      1640301.49      7007146.48
      1640160.83      7007040.31      1639944.24      7006528.32
      1639510.46      7006140.45      1639508.54      7005839.46
      1639696.86      7005644.06      1639853.80      7005327.50
      1639853.78      7005098.50      1639805.21      7005019.73
      1639802.83      7004743.44      1639618.21      7004551.63
      1639457.45      7004443.47      1639265.50      7004436.78
      1639199.02      7004390.36      1639106.58      7004384.18
      1638845.32      7004227.22      1638715.76      7004097.68
      1638605.65      7003874.08      1638655.50      7003577.83
      1638605.52      7003472.78      1638604.01      7003198.29
      1638509.96      7003132.65      1638505.00      7003088.00

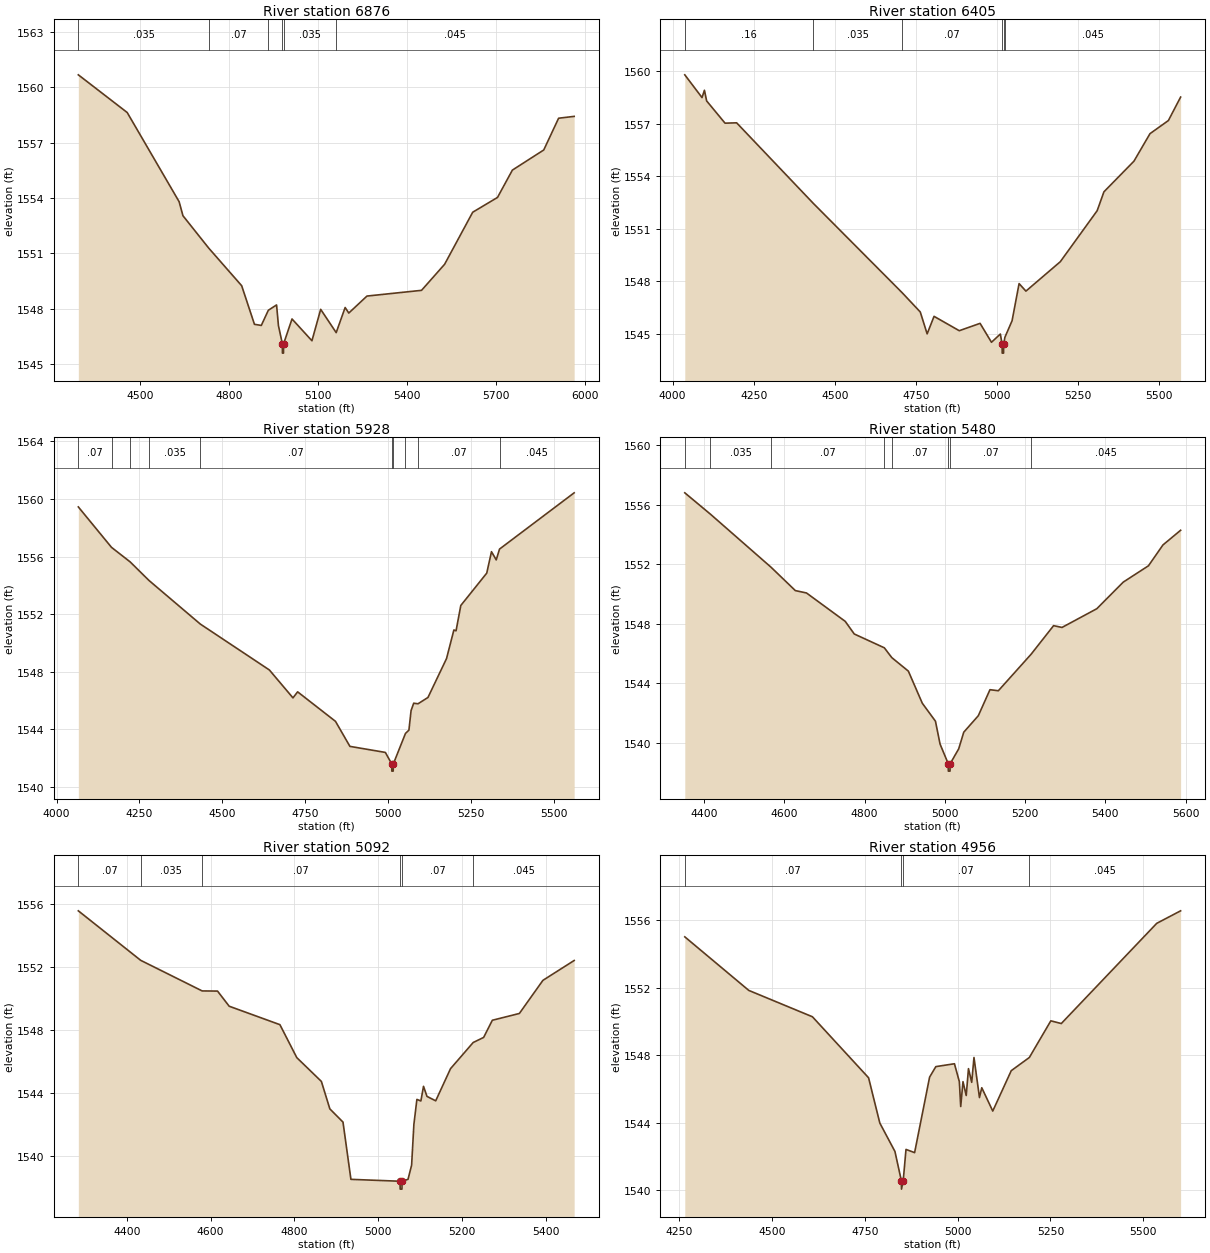
Type RM Length L Ch R = 1,6876,471,471,471
BEGIN DESCRIPTION:
Chimney Creek 1154 14.0
END DESCRIPTION:
XS GIS Cut Line= 3
      1641404.31      7007423.58      1641049.71      7008037.30
      1640615.26      7008897.52
#Sta/Elev= 30
  4291.2 1560.67  4456.0 1558.63  4631.2 1553.80  4644.1 1553.04  4730.9 1551.29
  4842.2 1549.25  4885.3 1547.16  4908.4 1547.10  4932.1 1547.92  4959.9 1548.21
  4966.2 1547.09  4979.5 1546.10  4979.7 1545.60  4983.2 1545.60  4983.5 1546.10
  5012.0 1547.45  5079.2 1546.27  5108.7 1547.97  5161.0 1546.71  5191.2 1548.07
  5203.5 1547.77  5264.8 1548.69  5448.9 1549.00  5526.7 1550.41  5621.5 1553.23
  5705.1 1554.03  5755.3 1555.51  5861.1 1556.60  5911.3 1558.32  5963.7 1558.42
#Mann=6,-1,0
  4291.2   0.035       0  4730.9    0.07       0  4932.1   0.035       0
  4979.5   0.035       0  4983.5   0.035       0  5161.0   0.045       0
Bank Sta=4979.5,4983.5
Exp/Cntr=0.3,0.1

Type RM Length L Ch R = 1,6405,477,477,477
BEGIN DESCRIPTION:
Mapping XS b3f5be64
END DESCRIPTION:
XS GIS Cut Line= 3
      1641302.72      7007280.39      1640641.28      7007993.91
      1640266.30      7008402.74
#Sta/Elev= 30
  4037.8 1559.78  4090.9 1558.48  4098.3 1558.90  4105.1 1558.29  4161.8 1557.02
  4197.5 1557.04  4433.8 1552.44  4707.5 1547.34  4763.3 1546.24  4784.5 1544.99
  4805.8 1545.99  4883.5 1545.17  4947.6 1545.59  4982.7 1544.51  5010.1 1544.98
  5015.5 1544.39  5015.8 1543.89  5019.9 1543.89  5020.3 1544.39  5024.0 1544.79
  5046.2 1545.74  5067.8 1547.86  5088.8 1547.43  5194.8 1549.11  5308.3 1552.02
  5329.2 1553.10  5421.7 1554.85  5471.1 1556.42  5527.8 1557.17  5565.5 1558.51
#Mann=6,-1,0
  4037.8    0.16       0  4433.8   0.035       0  4707.5    0.07       0
  5015.5    0.07       0  5020.3    0.07       0  5024.0   0.045       0
Bank Sta=5015.5,5020.3
Exp/Cntr=0.3,0.1

Type RM Length L Ch R = 1,5928,448,448,448
BEGIN DESCRIPTION:
Mapping XS 3332eb1f
END DESCRIPTION:
XS GIS Cut Line= 3
      1641136.11      7007111.07      1640393.89      7007686.62
      1639966.78      7008040.81
#Sta/Elev= 30
  4065.7 1559.45  4165.7 1556.64  4221.9 1555.63  4278.6 1554.34  4433.3 1551.31
  4641.4 1548.12  4712.5 1546.18  4726.5 1546.60  4840.6 1544.55  4884.1 1542.81
  4990.9 1542.39  5010.1 1541.59  5010.4 1541.09  5014.5 1541.09  5014.9 1541.59
  5051.5 1543.71  5061.9 1543.94  5068.4 1545.30  5076.3 1545.81  5089.3 1545.77
  5119.3 1546.21  5175.2 1548.91  5197.4 1550.90  5203.9 1550.84  5218.2 1552.60
  5296.4 1554.85  5310.7 1556.34  5325.0 1555.77  5334.9 1556.52  5559.8 1560.43
#Mann=10,-1,0
  4065.7    0.07       0  4165.7   0.035       0  4221.9    0.16       0
  4278.6   0.035       0  4433.3    0.07       0  5010.1    0.07       0
  5014.9    0.07       0  5051.5   0.045       0  5089.3    0.07       0
  5334.9   0.045       0
Bank Sta=5010.1,5014.9
Exp/Cntr=0.3,0.1

Type RM Length L Ch R = 1,5480,388,388,388
BEGIN DESCRIPTION:
Mapping XS 4697b113
END DESCRIPTION:
XS GIS Cut Line= 3
      1640930.60      7006955.05      1640351.14      7007252.37
      1639868.57      7007581.30
#Sta/Elev= 30
  4352.1 1556.81  4416.1 1555.37  4567.1 1551.80  4627.5 1550.23  4655.3 1550.07
  4751.8 1548.16  4774.3 1547.31  4849.2 1546.38  4867.8 1545.72  4909.1 1544.81
  4943.8 1542.65  4976.6 1541.44  4988.1 1539.90  5008.4 1538.58  5008.7 1538.08
  5012.9 1538.08  5013.3 1538.58  5034.5 1539.58  5047.1 1540.70  5083.4 1541.81
  5112.4 1543.56  5133.3 1543.49  5215.0 1545.95  5270.9 1547.87  5291.9 1547.75
  5378.6 1549.01  5444.4 1550.80  5507.3 1551.90  5543.3 1553.30  5587.4 1554.29
#Mann=8,-1,0
  4352.1    0.07       0  4416.1   0.035       0  4567.1    0.07       0
  4849.2    0.16       0  4867.8    0.07       0  5008.4    0.07       0
  5013.3    0.07       0  5215.0   0.045       0
Bank Sta=5008.4,5013.3
Exp/Cntr=0.3,0.1

Type RM Length L Ch R = 1,5092,136,136,136
BEGIN DESCRIPTION:
Mapping XS 3d91e1f3
END DESCRIPTION:
XS GIS Cut Line= 5
      1640826.39      7006800.99      1640273.01      7006946.38
      1640127.61      7006963.75      1640095.06      7007052.72
      1639871.52      7007347.89
#Sta/Elev= 30
  4284.2 1555.54  4433.1 1552.40  4579.8 1550.46  4616.5 1550.45  4644.3 1549.49
  4765.4 1548.32  4805.7 1546.23  4864.4 1544.72  4884.6 1542.98  4916.0 1542.14
  4934.9 1538.51  5052.1 1538.39  5052.5 1537.89  5056.7 1537.89  5057.1 1538.39
  5071.2 1538.51  5079.8 1539.41  5085.2 1541.99  5092.4 1543.58  5101.9 1543.48
  5108.2 1544.41  5116.5 1543.77  5137.3 1543.49  5172.7 1545.53  5226.8 1547.19
  5251.7 1547.51  5272.5 1548.60  5337.0 1549.03  5393.2 1551.13  5467.8 1552.39
#Mann=6,-1,0
  4284.2    0.07       0  4433.1   0.035       0  4579.8    0.07       0
  5052.1    0.07       0  5057.1    0.07       0  5226.8   0.045       0
Bank Sta=5052.1,5057.1
Exp/Cntr=0.3,0.1

Type RM Length L Ch R = 1,4956,98,98,98
BEGIN DESCRIPTION:
Mapping XS 4bbcb3f8
END DESCRIPTION:
XS GIS Cut Line= 5
      1640796.04      7006761.92      1640184.04      7006840.05
      1640064.68      7006848.73      1639984.38      7006905.15
      1639588.79      7007212.11
#Sta/Elev= 30
  4265.3 1555.00  4437.7 1551.83  4609.1 1550.27  4760.3 1546.66  4790.6 1543.98
  4831.3 1542.30  4848.6 1540.57  4849.0 1540.07  4853.6 1540.57  4861.1 1542.42
  4884.3 1542.23  4924.7 1546.70  4941.5 1547.32  4991.6 1547.49  5004.8 1546.43
  5008.5 1544.96  5014.6 1546.43  5023.3 1545.61  5029.4 1547.20  5038.1 1546.39
  5044.2 1547.86  5059.0 1545.49  5065.2 1546.07  5094.8 1544.69  5144.6 1547.08
  5193.3 1547.86  5251.2 1550.03  5279.4 1549.87  5536.5 1555.80  5600.8 1556.54
#Mann=4,-1,0
  4265.3    0.07       0  4848.6    0.07       0  4853.6    0.07       0
  5193.3   0.045       0
Bank Sta=4848.6,4853.6
Exp/Cntr=0.3,0.1

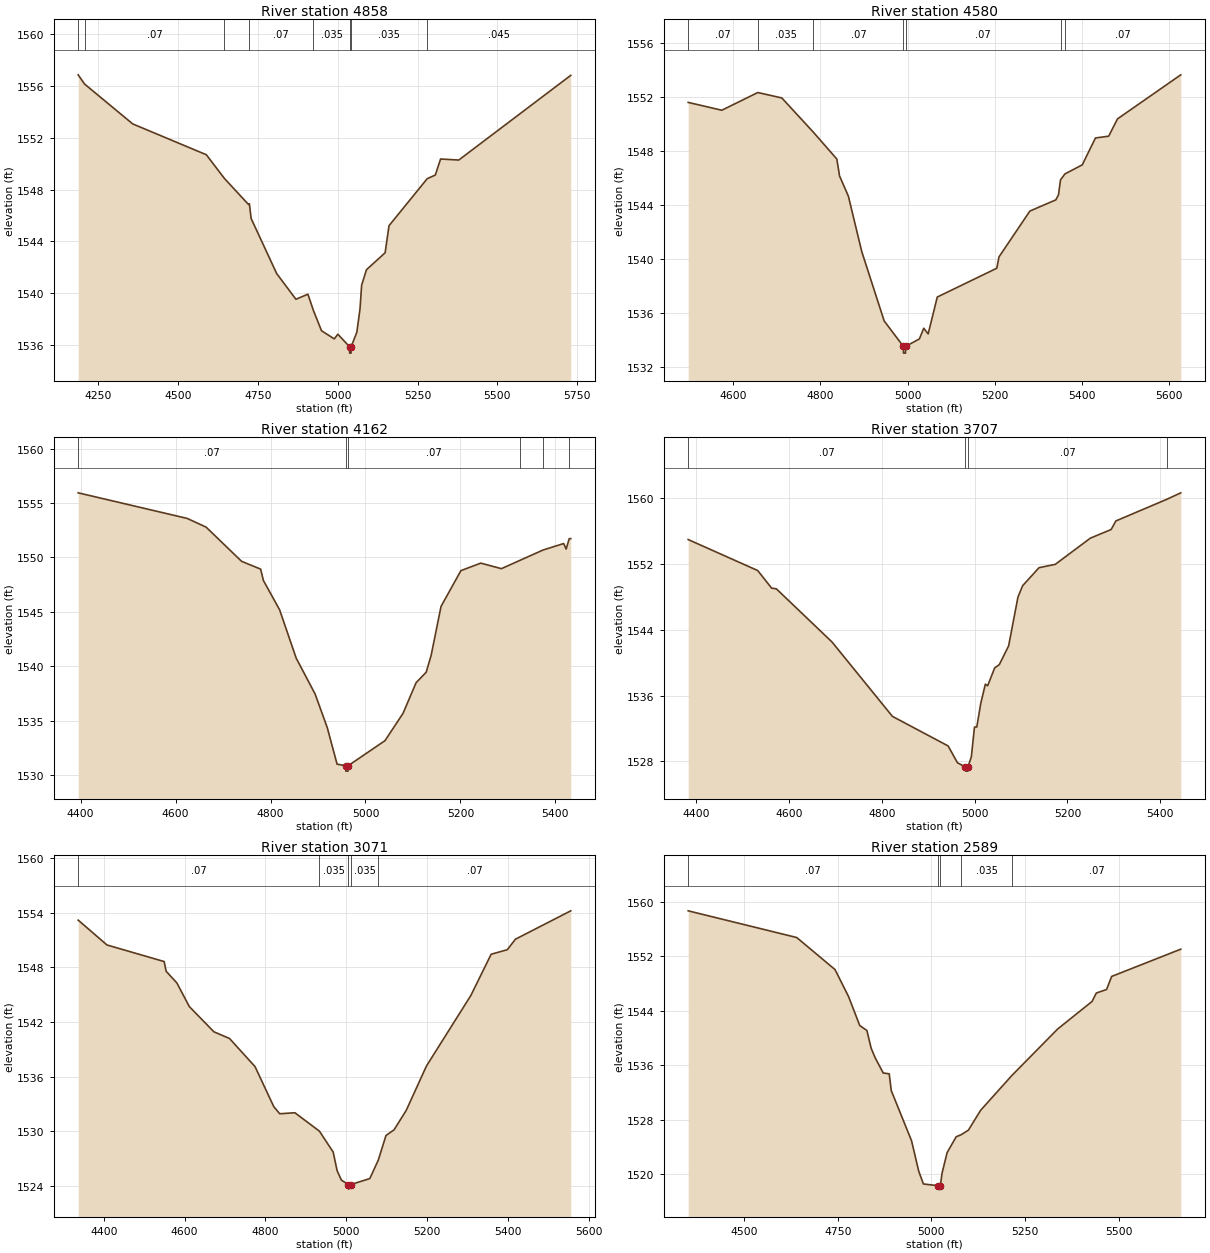
Type RM Length L Ch R = 1,4858,278,278,278
BEGIN DESCRIPTION:
Mapping XS ce152e29
END DESCRIPTION:
XS GIS Cut Line= 4
      1640865.50      7006714.18      1640140.63      7006753.24
      1640053.83      7006753.24      1639331.13      7006848.73
#Sta/Elev= 30
  4187.8 1556.87  4207.8 1556.16  4358.5 1553.08  4588.9 1550.70  4645.5 1548.87
  4720.9 1546.86  4723.7 1546.91  4729.1 1545.78  4809.2 1541.52  4869.3 1539.54
  4906.8 1539.93  4924.0 1538.68  4949.4 1537.11  4989.3 1536.48  5000.5 1536.84
  5037.0 1535.88  5037.5 1535.38  5041.9 1535.38  5042.3 1535.88  5059.9 1536.99
  5069.9 1538.79  5075.0 1540.63  5090.1 1541.82  5148.5 1543.13  5160.7 1545.22
  5280.2 1548.85  5305.5 1549.13  5322.1 1550.37  5379.0 1550.29  5729.5 1556.83
#Mann=8,-1,0
  4187.8   0.035       0  4207.8    0.07       0  4645.5   0.035       0
  4720.9    0.07       0  4924.0   0.035       0  5037.0   0.035       0
  5042.3   0.035       0  5280.2   0.045       0
Bank Sta=5037,5042.3
Exp/Cntr=0.3,0.1

Type RM Length L Ch R = 1,4580,418,418,418
BEGIN DESCRIPTION:
Mapping XS 44b0d219
END DESCRIPTION:
XS GIS Cut Line= 3
      1640425.84      7006418.38      1639932.82      7006513.86
      1639311.27      7006602.41
#Sta/Elev= 30
  4496.5 1551.61  4573.6 1551.03  4656.2 1552.34  4711.3 1551.94  4783.8 1549.40
  4837.5 1547.42  4843.7 1546.17  4864.0 1544.67  4894.6 1540.58  4946.1 1535.44
  4990.1 1533.56  4990.5 1533.06  4995.0 1533.06  4995.4 1533.56  5026.8 1534.11
  5036.9 1534.90  5047.0 1534.48  5067.9 1537.21  5204.4 1539.34  5209.5 1540.18
  5280.3 1543.57  5339.9 1544.40  5346.0 1544.78  5350.6 1545.88  5360.8 1546.32
  5400.5 1546.99  5430.8 1548.98  5461.1 1549.11  5481.3 1550.39  5626.5 1553.65
#Mann=7,-1,0
  4496.5    0.07       0  4656.2   0.035       0  4783.8    0.07       0
  4990.1    0.07       0  4995.4    0.07       0  5350.6   0.035       0
  5360.8    0.07       0
Bank Sta=4990.1,4995.4
Exp/Cntr=0.3,0.1

Type RM Length L Ch R = 1,4162,455,455,455
BEGIN DESCRIPTION:
Mapping XS b67f326c
END DESCRIPTION:
XS GIS Cut Line= 3
      1640201.96      7006093.71      1639618.58      7006249.97
      1639203.65      7006376.71
#Sta/Elev= 30
  4394.7 1555.93  4624.2 1553.58  4664.2 1552.78  4739.1 1549.63  4779.1 1548.92
  4785.0 1547.87  4819.1 1545.18  4854.0 1540.74  4894.0 1537.43  4919.5 1534.35
  4940.2 1530.99  4958.2 1530.85  4958.7 1530.35  4963.2 1530.35  4963.6 1530.85
  5041.1 1533.15  5079.1 1535.66  5106.7 1538.48  5127.9 1539.44  5138.3 1540.98
  5159.2 1545.49  5201.1 1548.78  5242.9 1549.47  5286.4 1548.96  5324.8 1549.71
  5374.5 1550.68  5417.6 1551.27  5422.8 1550.76  5429.3 1551.72  5432.5 1551.72
#Mann=6,-1,0
  4394.7    0.07       0  4958.2    0.07       0  4963.6    0.07       0
  5324.8   0.035       0  5374.5    0.07       0  5429.3   0.035       0
Bank Sta=4958.2,4963.6
Exp/Cntr=0.3,0.1

Type RM Length L Ch R = 1,3707,636,636,636
BEGIN DESCRIPTION:
Mapping XS 378c489f
END DESCRIPTION:
XS GIS Cut Line= 3
      1640124.72      7005863.17      1639506.66      7005840.60
      1639065.64      7005880.53
#Sta/Elev= 30
  4383.0 1554.97  4532.8 1551.20  4562.8 1549.06  4572.9 1548.98  4692.9 1542.51
  4823.0 1533.47  4943.1 1529.87  4963.1 1527.83  4980.4 1527.31  4980.8 1526.81
  4985.4 1526.81  4985.8 1527.31  4993.1 1528.57  4999.8 1532.17  5004.8 1532.17
  5013.2 1535.01  5023.2 1537.38  5028.2 1537.19  5043.3 1539.36  5053.3 1539.76
  5073.4 1542.04  5093.5 1547.98  5103.6 1549.36  5138.9 1551.55  5173.8 1551.95
  5249.5 1555.14  5294.3 1556.19  5304.4 1557.23  5414.1 1559.86  5444.3 1560.65
#Mann=4,-1,0
  4383.0    0.07       0  4980.4    0.07       0  4985.8    0.07       0
  5414.1   0.035       0
Bank Sta=4980.4,4985.8
Exp/Cntr=0.3,0.1

Type RM Length L Ch R = 1,3071,482,482,482
BEGIN DESCRIPTION:
Mapping XS a0e3929c
END DESCRIPTION:
XS GIS Cut Line= 3
      1640504.95      7005453.45      1639853.89      7005329.75
      1639298.06      7005312.44
#Sta/Elev= 30
  4336.7 1553.18  4407.9 1550.45  4549.4 1548.63  4554.4 1547.56  4580.9 1546.28
  4611.8 1543.68  4672.6 1540.91  4711.1 1540.18  4774.3 1537.09  4820.7 1532.69
  4835.4 1531.91  4872.9 1532.02  4933.6 1530.00  4967.7 1527.70  4977.4 1525.66
  4988.1 1524.61  5005.5 1524.13  5006.0 1523.63  5011.0 1524.13  5058.3 1524.79
  5079.2 1526.81  5098.3 1529.52  5118.4 1530.15  5148.4 1532.28  5198.4 1537.15
  5308.4 1544.91  5358.5 1549.43  5398.5 1549.93  5418.5 1551.08  5555.5 1554.20
#Mann=5,-1,0
  4336.7    0.07       0  4933.6   0.035       0  5005.5   0.035       0
  5011.0   0.035       0  5079.2    0.07       0
Bank Sta=5005.5,5011
Exp/Cntr=0.3,0.1

Type RM Length L Ch R = 1,2589,587,587,587
BEGIN DESCRIPTION:
Mapping XS 722a94f1
END DESCRIPTION:
XS GIS Cut Line= 3
      1640410.29      7004627.50      1639806.14      7004863.60
      1639168.67      7005061.08
#Sta/Elev= 30
  4350.2 1558.68  4640.2 1554.76  4742.4 1550.06  4778.7 1546.09  4808.5 1541.84
  4827.6 1541.11  4839.0 1538.51  4849.8 1537.10  4871.2 1534.87  4887.3 1534.75
  4892.7 1532.29  4947.0 1524.91  4966.1 1520.45  4978.6 1518.58  5018.1 1518.32
  5018.5 1517.82  5023.9 1518.32  5028.4 1520.16  5041.9 1523.18  5066.2 1525.51
  5079.8 1525.82  5098.8 1526.48  5131.4 1529.39  5215.2 1534.52  5337.5 1541.34
  5429.3 1545.38  5440.5 1546.61  5467.9 1547.13  5481.6 1549.05  5666.2 1553.05
#Mann=5,-1,0
  4350.2    0.07       0  5018.1    0.07       0  5023.9    0.07       0
  5079.8   0.035       0  5215.2    0.07       0
Bank Sta=5018.1,5023.9
Exp/Cntr=0.3,0.1

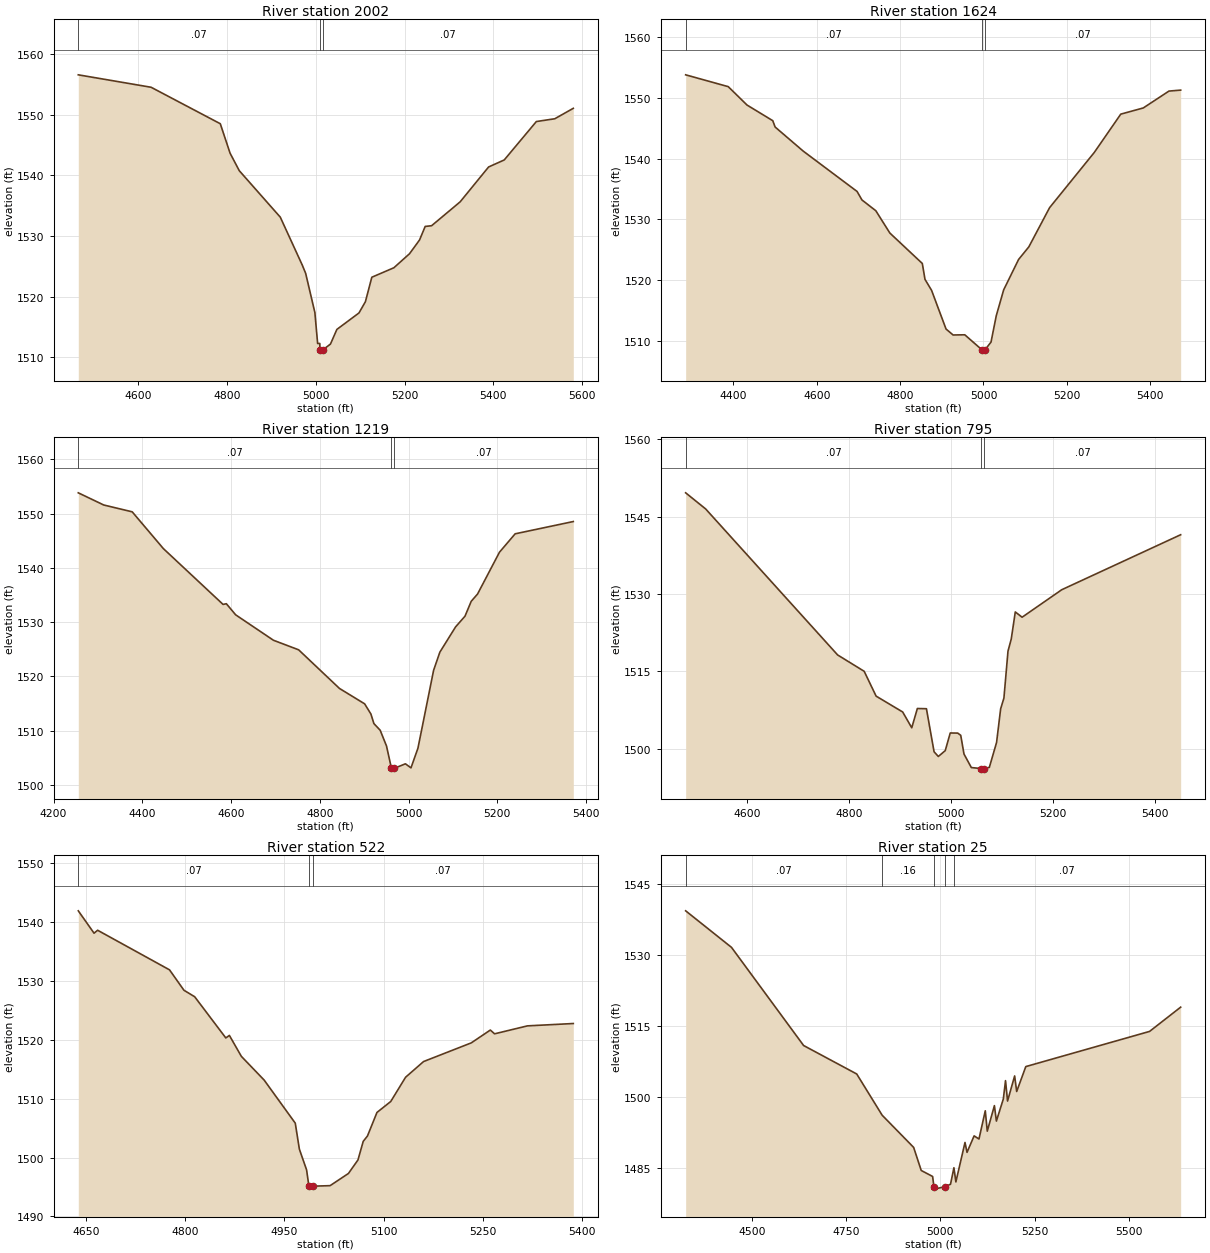
Type RM Length L Ch R = 1,2002,378,378,378
BEGIN DESCRIPTION:
Mapping XS 0cc13cbd
END DESCRIPTION:
XS GIS Cut Line= 3
      1639802.64      7004033.77      1639451.98      7004450.41
      1639101.27      7004901.81
#Sta/Elev= 30
  4464.3 1556.57  4628.5 1554.52  4784.5 1548.51  4806.6 1543.65  4827.4 1540.76
  4919.8 1533.11  4969.2 1525.24  4977.0 1523.85  4997.8 1517.39  5004.0 1512.29
  5008.9 1512.29  5009.2 1511.20  5009.7 1510.70  5015.1 1511.20  5032.9 1512.19
  5047.4 1514.61  5097.2 1517.32  5111.7 1519.17  5126.2 1523.21  5175.9 1524.77
  5211.2 1527.08  5233.8 1529.35  5246.5 1531.58  5261.0 1531.70  5325.3 1535.63
  5389.5 1541.38  5424.8 1542.54  5497.2 1548.87  5538.8 1549.33  5580.5 1551.05
#Mann=3,-1,0
  4464.3    0.07       0  5009.2    0.07       0  5015.1    0.07       0
Bank Sta=5009.2,5015.1
Exp/Cntr=0.3,0.1

Type RM Length L Ch R = 1,1624,405,405,405
BEGIN DESCRIPTION:
Mapping XS 7f36ec6f
END DESCRIPTION:
XS GIS Cut Line= 3
      1639413.80      7003738.57      1639094.34      7004387.91
      1638931.13      7004821.97
#Sta/Elev= 30
  4285.7 1553.83  4387.9 1551.88  4432.9 1548.85  4494.7 1546.27  4500.3 1545.23
  4567.7 1541.26  4696.9 1534.61  4708.6 1533.21  4741.9 1531.43  4775.5 1527.76
  4853.4 1522.74  4859.8 1520.13  4875.7 1518.30  4910.3 1511.94  4927.2 1510.96
  4955.3 1510.99  4997.2 1508.47  4997.7 1507.97  5003.2 1508.47  5018.2 1509.79
  5030.8 1514.14  5048.5 1518.39  5084.3 1523.40  5108.9 1525.48  5158.7 1531.94
  5265.9 1541.04  5329.4 1547.35  5383.4 1548.37  5445.0 1551.15  5473.1 1551.31
#Mann=3,-1,0
  4285.7    0.07       0  4997.2    0.07       0  5003.2    0.07       0
Bank Sta=4997.2,5003.2
Exp/Cntr=0.3,0.1

Type RM Length L Ch R = 1,1219,424,424,424
BEGIN DESCRIPTION:
Mapping XS 56b656bb
END DESCRIPTION:
XS GIS Cut Line= 3
      1639274.91      7003606.64      1638771.42      7004162.21
      1638514.48      7004422.62
#Sta/Elev= 30
  4255.6 1553.82  4312.9 1551.58  4377.1 1550.32  4447.4 1543.54  4581.9 1533.26
  4589.3 1533.39  4610.2 1531.35  4695.4 1526.66  4752.2 1524.90  4844.1 1517.79
  4900.9 1514.95  4915.1 1513.07  4921.8 1511.31  4936.0 1510.08  4950.2 1507.19
  4961.4 1503.05  4961.9 1502.55  4967.4 1503.05  4992.8 1503.90  5005.4 1503.15
  5021.1 1506.78  5056.4 1521.13  5070.5 1524.47  5105.9 1529.12  5127.1 1531.09
  5141.2 1533.84  5155.4 1535.17  5204.9 1542.89  5240.2 1546.27  5371.2 1548.53
#Mann=3,-1,0
  4255.6    0.07       0  4961.4    0.07       0  4967.4    0.07       0
Bank Sta=4961.4,4967.4
Exp/Cntr=0.3,0.1

Type RM Length L Ch R = 1,795,273,273,273
BEGIN DESCRIPTION:
Mapping XS de8895f6
END DESCRIPTION:
XS GIS Cut Line= 3
      1639080.90      7003581.91      1638596.51      7003795.46
      1638253.44      7004073.55
#Sta/Elev= 30
  4479.4 1549.61  4518.6 1546.49  4777.5 1518.20  4829.6 1515.03  4853.0 1510.22
  4905.1 1507.15  4922.9 1504.09  4933.9 1507.82  4951.7 1507.78  4966.7 1499.44
  4975.0 1498.53  4988.6 1499.66  4998.4 1503.08  5013.0 1503.06  5019.0 1502.63
  5025.4 1499.00  5039.8 1496.38  5059.1 1496.19  5059.6 1495.69  5065.1 1496.19
  5075.1 1496.42  5089.3 1501.25  5097.3 1507.77  5103.7 1509.84  5111.7 1518.94
  5118.1 1521.29  5126.0 1526.53  5139.4 1525.51  5217.2 1530.84  5450.4 1541.49
#Mann=3,-1,0
  4479.4    0.07       0  5059.1    0.07       0  5065.1    0.07       0
Bank Sta=5059.1,5065.1
Exp/Cntr=0.3,0.1

Type RM Length L Ch R = 1,522,497,497,497
BEGIN DESCRIPTION:
Mapping XS f1e9684a
END DESCRIPTION:
XS GIS Cut Line= 3
      1638981.57      7003393.46      1638649.55      7003536.69
      1638348.98      7003778.87
#Sta/Elev= 30
  4638.6 1541.93  4662.4 1538.13  4667.8 1538.63  4776.4 1531.90  4798.2 1528.43
  4814.4 1527.33  4861.4 1520.33  4866.8 1520.76  4884.9 1517.20  4919.3 1513.17
  4966.3 1505.85  4972.5 1501.43  4983.4 1497.91  4986.9 1495.14  4987.4 1494.64
  4992.9 1495.14  5018.9 1495.23  5046.6 1497.30  5061.0 1499.60  5068.9 1502.75
  5075.3 1503.66  5089.7 1507.67  5110.5 1509.53  5132.9 1513.65  5160.1 1516.32
  5232.1 1519.49  5260.9 1521.67  5267.3 1521.03  5316.9 1522.38  5386.2 1522.78
#Mann=3,-1,0
  4638.6    0.07       0  4986.9    0.07       0  4992.9    0.07       0
Bank Sta=4986.9,4992.9
Exp/Cntr=0.3,0.1

Type RM Length L Ch R = 1,25,0,0,0
BEGIN DESCRIPTION:
Chimney Creek 1154 1.0
END DESCRIPTION:
XS GIS Cut Line= 3
      1639175.78      7003035.39      1638504.55      7003113.00
      1638267.09      7003704.52
#Sta/Elev= 30
  4324.3 1539.29  4445.9 1531.59  4637.2 1510.91  4778.1 1504.91  4845.6 1496.22
  4929.1 1489.44  4949.2 1484.58  4979.4 1483.32  4982.9 1481.15  4983.4 1480.65
  5011.6 1481.15  5026.9 1481.68  5035.9 1485.16  5041.1 1482.17  5065.3 1490.48
  5070.7 1488.40  5089.5 1491.87  5102.4 1491.21  5119.1 1497.16  5124.4 1492.86
  5143.3 1498.24  5148.6 1494.99  5167.0 1499.65  5172.8 1503.51  5178.2 1499.21
  5197.0 1504.50  5202.4 1501.22  5226.6 1506.47  5554.9 1513.88  5637.4 1518.99
#Mann=5,-1,0
  4324.3    0.07       0  4845.6    0.16       0  4982.9    0.07       0
  5011.6    0.16       0  5035.9    0.07       0
Bank Sta=4982.9,5011.6
Exp/Cntr=0.3,0.1

Chan Stop Cuts=-1