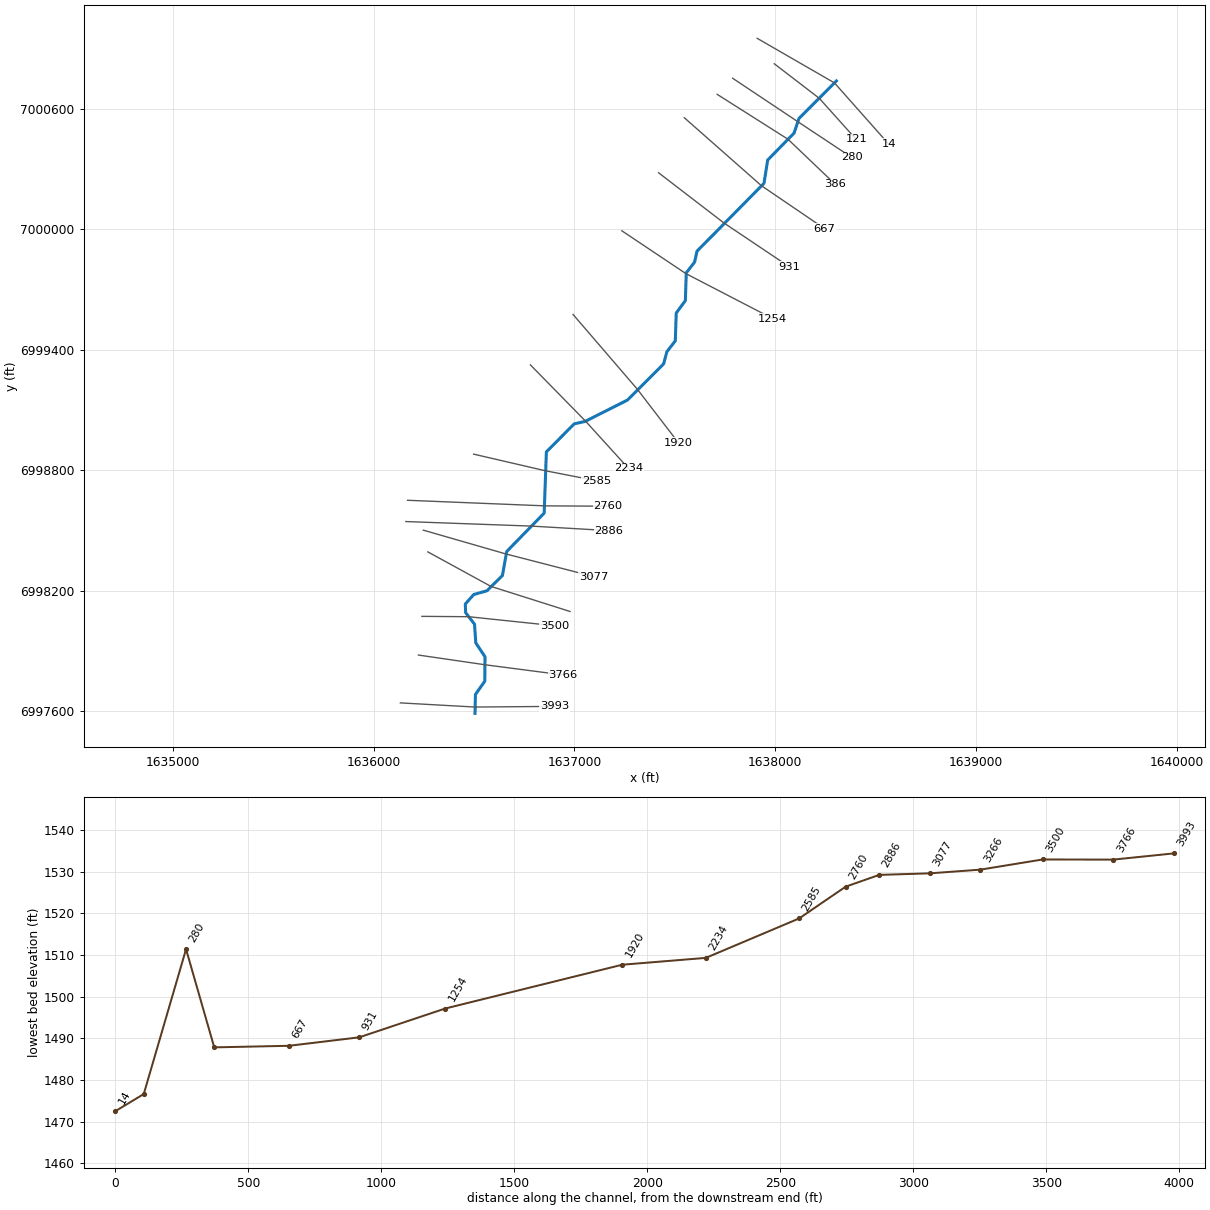
--- Chimney Creek 1155.prj (project) ---

Proj Title=Chimney Creek 1155 Base Level Engineering
Current Plan=p01
Default Exp/Contr=0.3,0.1
English Units
Geom File=g01
Flow File=f01
Plan File=p01
BEGIN DESCRIPTION:
Chimney Creek 1155
END DESCRIPTION:

--- Chimney Creek 1155.p01 (plan) ---

Plan Title=Multiple Run
Short Identifier=Multiple
Geom File=g01
Flow File=f01
Subcritical Flow
K Sum by GR= 0
Std Step Tol= 0.01
Critical Tol= 0.01
Num of Std Step Trials= 20
Max Error Tol= 0.3
Flow Tol Ratio= 0.001
Split Flow NTrial= 30
Split Flow Tol= 0.02
Split Flow Ratio= 0.02
Log Output Level= 0
Friction Slope Method= 1
Unsteady Friction Slope Method= 2
Unsteady Bridges Friction Slope Method= 1
Parabolic Critical Depth
Global Vel Dist=  1 , 1 , 1
Global Log Level= 0
CheckData=True
Encroach Param= -1, 0, 0, 0
BEGIN DESCRIPTION:
Multiple Run
END DESCRIPTION:

--- Chimney Creek 1155.f01 (steady flow) ---

Flow Title=Multiple
Number of Profiles=7
Profile Names=10-year,25-year,50-year,1pct_min,100-year,1pct_plu,500-year
River Rch & RM= Chimney Creek 11,Reach-1,3993
     223     305     371     225     450     897     668
River Rch & RM= Chimney Creek 11,Reach-1,2585
     336     473     588     364     725    1447    1120
River Rch & RM= Chimney Creek 11,Reach-1,14
    1358    1976    2509    1577    3146    6277    5011
Boundary for River Rch & Prof#=Chimney Creek 11,Reach-1,1
Up Type=0
Dn Type=3
Dn Slope=0.005
Boundary for River Rch & Prof#=Chimney Creek 11,Reach-1,2
Up Type=0
Dn Type=3
Dn Slope=0.005
Boundary for River Rch & Prof#=Chimney Creek 11,Reach-1,3
Up Type=0
Dn Type=3
Dn Slope=0.005
Boundary for River Rch & Prof#=Chimney Creek 11,Reach-1,4
Up Type=0
Dn Type=3
Dn Slope=0.005
Boundary for River Rch & Prof#=Chimney Creek 11,Reach-1,5
Up Type=0
Dn Type=3
Dn Slope=0.005
Boundary for River Rch & Prof#=Chimney Creek 11,Reach-1,6
Up Type=0
Dn Type=3
Dn Slope=0.005
Boundary for River Rch & Prof#=Chimney Creek 11,Reach-1,7
Up Type=0
Dn Type=3
Dn Slope=0.005

--- Chimney Creek 1155.g01 (geometry) ---

Geom Title=Existing Conditions

River Reach=Chimney Creek 11,Reach-1
Reach XY= 30
      1636505.00      6997588.00      1636507.10      6997682.13
      1636553.81      6997748.50      1636554.81      6997869.72
      1636508.86      6997939.60      1636502.62      6998032.04
      1636458.33      6998089.78      1636456.66      6998132.56
      1636498.57      6998179.96      1636564.68      6998198.78
      1636641.61      6998274.67      1636662.86      6998394.17
      1636849.54      6998585.55      1636860.46      6998890.45
      1636998.94      6999029.86      1637053.26      6999042.19
      1637264.68      6999148.76      1637444.24      6999328.32
      1637461.14      6999390.17      1637502.64      6999443.52
      1637507.27      6999582.06      1637552.73      6999643.94
      1637557.25      6999782.07      1637598.86      6999835.83
      1637610.83      6999890.30      1637944.48      7000228.21
      1637962.86      7000344.17      1638094.22      7000478.32
      1638118.63      7000551.21      1638305.00      7000738.00

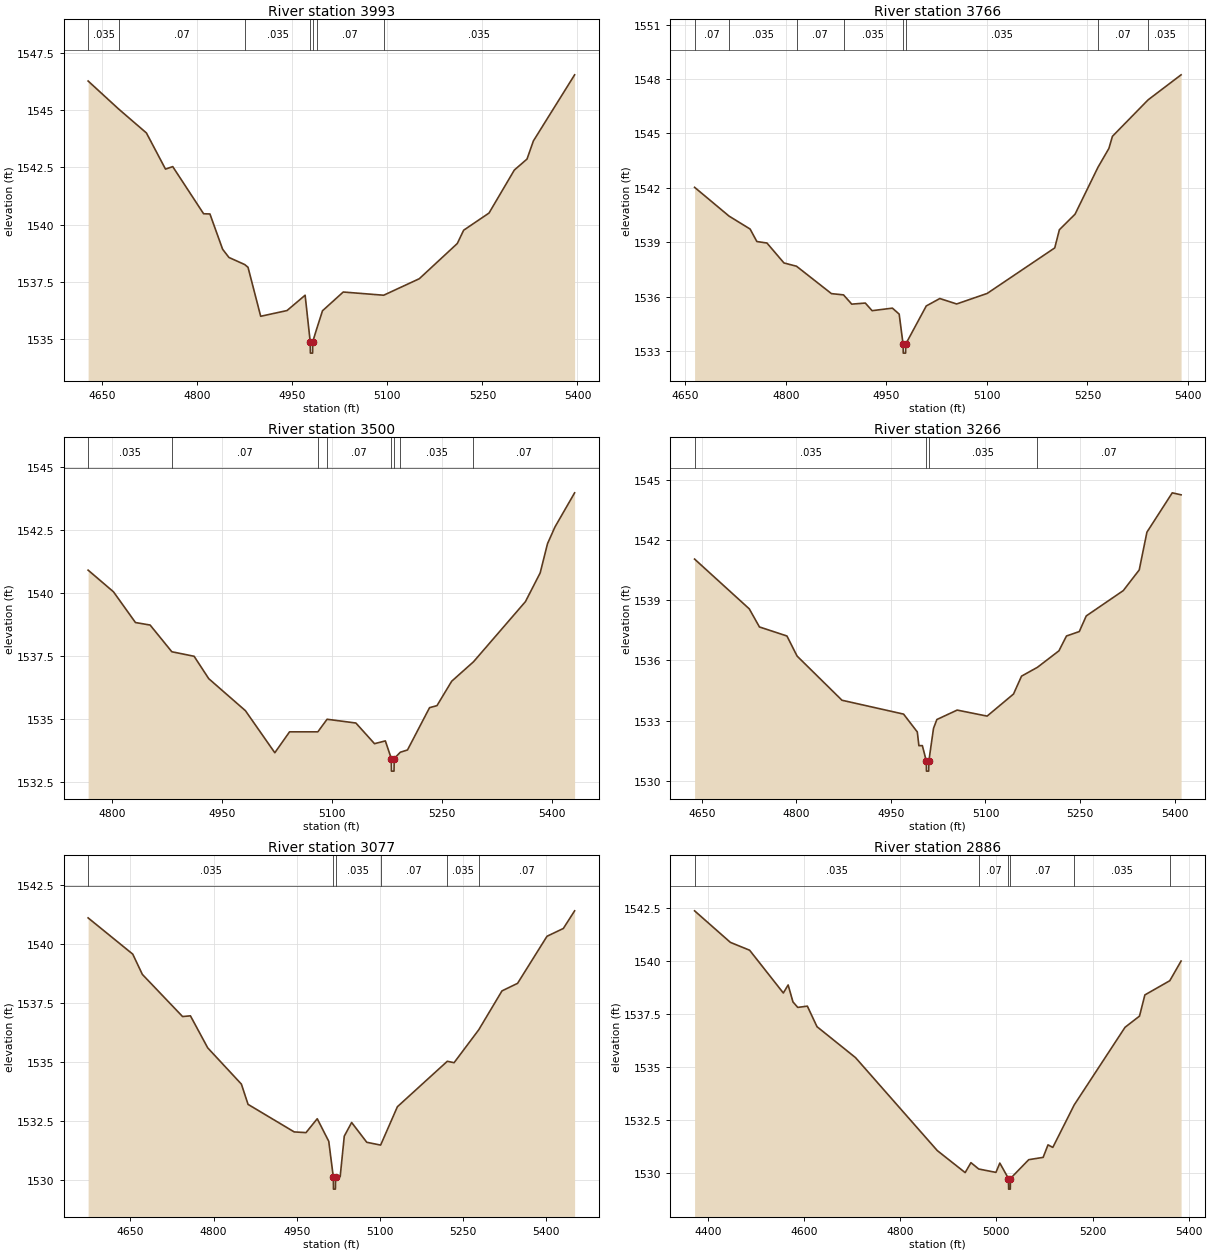
Type RM Length L Ch R = 1,3993,227,227,227
BEGIN DESCRIPTION:
Chimney Creek 1155 8.0
END DESCRIPTION:
XS GIS Cut Line= 3
      1636133.10      6997640.20      1636504.63      6997619.57
      1636900.12      6997622.84
#Sta/Elev= 30
  4627.9 1546.27  4676.3 1545.04  4719.9 1544.00  4750.0 1542.42  4761.4 1542.53
  4810.1 1540.47  4820.1 1540.46  4840.1 1538.92  4850.1 1538.56  4875.0 1538.25
  4880.2 1538.13  4900.2 1535.99  4941.7 1536.24  4970.3 1536.91  4978.3 1534.88
  4978.6 1534.38  4982.1 1534.38  4982.3 1534.88  4988.9 1535.47  4997.7 1536.23
  5030.4 1537.05  5094.2 1536.91  5150.4 1537.63  5210.4 1539.17  5220.4 1539.75
  5260.4 1540.50  5300.4 1542.38  5320.4 1542.86  5330.4 1543.65  5395.5 1546.54
#Mann=7,-1,0
  4627.9   0.035       0  4676.3    0.07       0  4875.0   0.035       0
  4978.3    0.07       0  4982.3   0.035       0  4988.9    0.07       0
  5094.2   0.035       0
Bank Sta=4978.3,4982.3
Exp/Cntr=0.3,0.1

Type RM Length L Ch R = 1,3766,266,266,266
BEGIN DESCRIPTION:
Mapping XS e4c710cd
END DESCRIPTION:
XS GIS Cut Line= 3
      1636223.05      6997878.55      1636556.41      6997829.93
      1636941.78      6997779.82
#Sta/Elev= 30
  4664.1 1542.03  4715.6 1540.44  4746.9 1539.73  4757.0 1539.04  4772.0 1538.96
  4797.4 1537.86  4816.1 1537.68  4868.2 1536.17  4886.2 1536.10  4898.5 1535.59
  4918.7 1535.65  4928.8 1535.23  4959.1 1535.37  4969.2 1535.04  4975.0 1533.39
  4975.3 1532.89  4978.8 1532.89  4979.0 1533.39  5009.6 1535.49  5029.8 1535.90
  5054.9 1535.60  5100.4 1536.18  5201.2 1538.69  5208.1 1539.69  5231.5 1540.55
  5265.6 1543.13  5281.9 1544.17  5287.2 1544.84  5340.4 1546.85  5389.6 1548.23
#Mann=8,-1,0
  4664.1    0.07       0  4715.6   0.035       0  4816.1    0.07       0
  4886.2   0.035       0  4975.0   0.035       0  4979.0   0.035       0
  5265.6    0.07       0  5340.4   0.035       0
Bank Sta=4975,4979
Exp/Cntr=0.3,0.1

Type RM Length L Ch R = 1,3500,234,234,234
BEGIN DESCRIPTION:
Mapping XS a7fdb147
END DESCRIPTION:
XS GIS Cut Line= 3
      1636240.43      6998071.25      1636473.08      6998069.51
      1636901.78      6998024.57
#Sta/Elev= 30
  4766.8 1540.90  4801.4 1540.04  4831.4 1538.82  4851.4 1538.72  4881.0 1537.66
  4911.4 1537.48  4931.4 1536.59  4981.4 1535.32  5021.5 1533.65  5041.6 1534.48
  5080.2 1534.48  5092.8 1534.98  5132.1 1534.83  5157.5 1534.01  5172.3 1534.12
  5180.4 1533.42  5180.6 1532.92  5184.1 1532.92  5184.4 1533.42  5192.7 1533.67
  5202.5 1533.76  5232.6 1535.44  5242.7 1535.52  5262.8 1536.49  5292.5 1537.26
  5363.4 1539.65  5383.5 1540.79  5393.5 1541.95  5403.6 1542.61  5430.5 1543.97
#Mann=8,-1,0
  4766.8   0.035       0  4881.0    0.07       0  5080.2   0.035       0
  5092.8    0.07       0  5180.4    0.07       0  5184.4    0.07       0
  5192.7   0.035       0  5292.5    0.07       0
Bank Sta=5180.4,5184.4
Exp/Cntr=0.3,0.1

Type RM Length L Ch R = 1,3266,189,189,189
BEGIN DESCRIPTION:
Mapping XS 1f0879e1
END DESCRIPTION:
XS GIS Cut Line= 3
      1636269.91      6998392.45      1636584.19      6998220.56
      1636978.32      6998095.55
#Sta/Elev= 30
  4638.6 1541.04  4725.4 1538.56  4741.5 1537.66  4785.1 1537.21  4801.2 1536.21
  4872.4 1534.01  4970.1 1533.32  4991.9 1532.43  4994.4 1531.75  4999.9 1531.75
  5006.2 1530.98  5006.4 1530.48  5009.9 1530.48  5010.2 1530.98  5017.6 1532.61
  5022.9 1533.05  5055.1 1533.52  5102.6 1533.22  5144.5 1534.32  5157.2 1535.21
  5182.4 1535.65  5216.5 1536.47  5228.5 1537.21  5248.8 1537.43  5259.9 1538.21
  5318.6 1539.47  5343.9 1540.50  5356.1 1542.38  5396.3 1544.34  5410.3 1544.24
#Mann=4,-1,0
  4638.6   0.035       0  5006.2   0.035       0  5010.2   0.035       0
  5182.4    0.07       0
Bank Sta=5006.2,5010.2
Exp/Cntr=0.3,0.1

Type RM Length L Ch R = 1,3077,191,191,191
BEGIN DESCRIPTION:
Mapping XS c96e9fe3
END DESCRIPTION:
XS GIS Cut Line= 3
      1636247.56      6998500.59      1636657.28      6998382.54
      1637094.78      6998269.69
#Sta/Elev= 30
  4573.6 1541.12  4654.2 1539.58  4671.5 1538.72  4744.1 1536.93  4758.3 1536.96
  4789.5 1535.60  4850.3 1534.06  4862.3 1533.20  4945.6 1532.03  4966.9 1532.00
  4987.2 1532.59  5008.0 1531.63  5016.3 1530.10  5016.5 1529.60  5020.0 1529.60
  5020.3 1530.10  5028.6 1530.13  5036.0 1531.85  5049.3 1532.43  5076.6 1531.59
  5101.6 1531.47  5131.9 1533.10  5222.0 1535.03  5234.2 1534.97  5278.8 1536.37
  5320.7 1538.02  5348.8 1538.34  5402.0 1540.34  5431.4 1540.67  5451.8 1541.42
#Mann=6,-1,0
  4573.6   0.035       0  5016.3   0.035       0  5020.3   0.035       0
  5101.6    0.07       0  5222.0   0.035       0  5278.8    0.07       0
Bank Sta=5016.3,5020.3
Exp/Cntr=0.3,0.1

Type RM Length L Ch R = 1,2886,126,126,126
BEGIN DESCRIPTION:
Mapping XS 05e81c55
END DESCRIPTION:
XS GIS Cut Line= 3
      1636160.54      6998543.47      1636783.84      6998520.90
      1637171.38      6998498.41
#Sta/Elev= 30
  4372.3 1542.36  4446.8 1540.87  4486.8 1540.50  4556.9 1538.48  4566.9 1538.86
  4576.9 1538.06  4586.9 1537.80  4606.9 1537.86  4626.9 1536.89  4707.0 1535.43
  4877.1 1531.04  4935.1 1530.00  4947.1 1530.47  4963.3 1530.17  4999.1 1530.01
  5007.2 1530.45  5025.2 1529.72  5025.5 1529.22  5029.0 1529.22  5029.2 1529.72
  5067.3 1530.61  5097.3 1530.72  5107.4 1531.31  5117.4 1531.19  5162.0 1533.20
  5267.6 1536.86  5297.7 1537.39  5308.9 1538.39  5360.7 1539.06  5384.2 1539.99
#Mann=6,-1,0
  4372.3   0.035       0  4963.3    0.07       0  5025.2    0.07       0
  5029.2    0.07       0  5162.0   0.035       0  5360.7    0.07       0
Bank Sta=5025.2,5029.2
Exp/Cntr=0.3,0.1

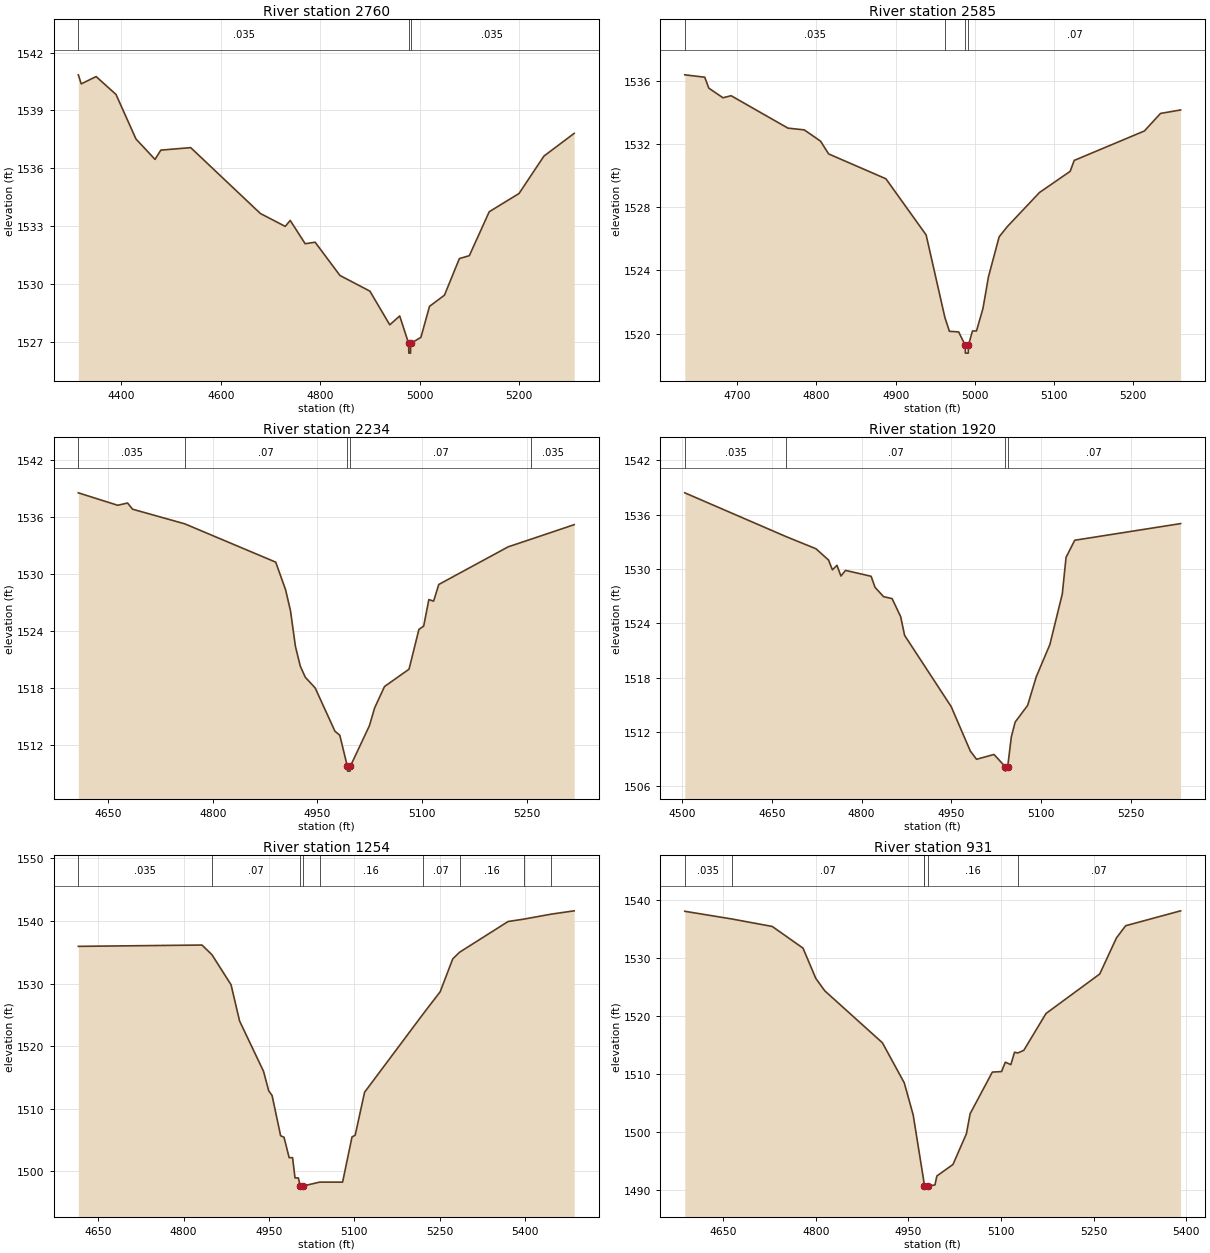
Type RM Length L Ch R = 1,2760,175,175,175
BEGIN DESCRIPTION:
Mapping XS 2804efb7
END DESCRIPTION:
XS GIS Cut Line= 3
      1636169.22      6998649.38      1636855.02      6998621.60
      1637165.75      6998619.86
#Sta/Elev= 30
  4313.2 1540.85  4319.0 1540.38  4349.0 1540.76  4389.0 1539.83  4429.1 1537.52
  4467.4 1536.46  4479.1 1536.94  4539.2 1537.07  4679.3 1533.65  4729.3 1532.98
  4739.3 1533.29  4769.4 1532.08  4789.4 1532.16  4839.4 1530.43  4899.5 1529.62
  4939.5 1527.87  4959.5 1528.33  4977.5 1526.90  4977.8 1526.40  4981.3 1526.40
  4981.5 1526.90  5002.1 1527.22  5019.5 1528.83  5049.5 1529.41  5079.5 1531.31
  5099.5 1531.46  5139.5 1533.74  5199.5 1534.69  5249.5 1536.63  5310.3 1537.81
#Mann=3,-1,0
  4313.2   0.035       0  4977.5   0.035       0  4981.5   0.035       0
Bank Sta=4977.5,4981.5
Exp/Cntr=0.3,0.1

Type RM Length L Ch R = 1,2585,351,351,351
BEGIN DESCRIPTION:
Mapping XS 8ddb1e25
END DESCRIPTION:
XS GIS Cut Line= 3
      1636498.02      6998879.27      1636853.90      6998796.81
      1637109.98      6998746.90
#Sta/Elev= 30
  4633.7 1536.36  4658.9 1536.21  4664.0 1535.52  4681.9 1534.91  4692.2 1535.04
  4764.0 1532.99  4784.6 1532.88  4805.1 1532.17  4815.4 1531.36  4887.7 1529.79
  4938.5 1526.24  4962.2 1521.02  4967.9 1520.15  4979.6 1520.11  4987.8 1519.27
  4988.1 1518.77  4991.7 1518.77  4991.9 1519.27  4997.0 1520.17  5002.1 1520.17
  5010.3 1521.60  5017.2 1523.59  5030.7 1526.12  5040.9 1526.76  5081.6 1528.92
  5120.4 1530.26  5125.5 1530.95  5214.1 1532.81  5234.5 1533.92  5259.9 1534.14
#Mann=4,-1,0
  4633.7   0.035       0  4962.2    0.07       0  4987.8    0.07       0
  4991.9    0.07       0
Bank Sta=4987.8,4991.9
Exp/Cntr=0.3,0.1

Type RM Length L Ch R = 1,2234,314,314,314
BEGIN DESCRIPTION:
Mapping XS 85ea6fd8
END DESCRIPTION:
XS GIS Cut Line= 3
      1636781.01      6999323.71      1637054.45      6999044.84
      1637269.29      6998808.30
#Sta/Elev= 30
  4607.5 1538.57  4663.9 1537.26  4678.0 1537.50  4685.1 1536.85  4759.9 1535.31
  4890.2 1531.28  4904.3 1528.38  4911.3 1526.19  4918.4 1522.43  4925.4 1520.34
  4932.6 1519.17  4946.7 1518.05  4975.0 1513.50  4982.0 1513.07  4992.8 1509.80
  4993.1 1509.30  4996.7 1509.30  4997.0 1509.80  5024.4 1514.08  5031.8 1515.94
  5046.0 1518.20  5081.1 1520.02  5095.3 1524.21  5102.1 1524.55  5109.5 1527.34
  5116.3 1527.18  5123.7 1528.93  5223.1 1532.89  5256.5 1533.71  5317.6 1535.22
#Mann=5,-1,0
  4607.5   0.035       0  4759.9    0.07       0  4992.8    0.07       0
  4997.0    0.07       0  5256.5   0.035       0
Bank Sta=4992.8,4997
Exp/Cntr=0.3,0.1

Type RM Length L Ch R = 1,1920,666,666,666
BEGIN DESCRIPTION:
Mapping XS e4e3e783
END DESCRIPTION:
XS GIS Cut Line= 3
      1636993.28      6999575.09      1637312.72      6999203.57
      1637519.30      6998934.49
#Sta/Elev= 30
  4504.3 1538.41  4673.8 1533.57  4723.7 1532.23  4744.6 1530.99  4751.2 1529.90
  4758.8 1530.40  4765.4 1529.22  4773.1 1529.84  4815.9 1529.19  4822.5 1527.96
  4836.7 1526.94  4851.0 1526.72  4865.3 1524.73  4871.9 1522.66  4949.8 1514.79
  4981.8 1509.88  4992.2 1508.97  5021.4 1509.50  5040.1 1508.16  5040.4 1507.66
  5044.3 1508.16  5050.4 1511.45  5056.8 1513.08  5077.6 1514.92  5092.1 1518.09
  5114.8 1521.64  5135.6 1527.23  5141.9 1531.28  5156.4 1533.17  5333.5 1535.01
#Mann=4,-1,0
  4504.3   0.035       0  4673.8    0.07       0  5040.1    0.07       0
  5044.3    0.07       0
Bank Sta=5040.1,5044.3
Exp/Cntr=0.3,0.1

Type RM Length L Ch R = 1,1254,323,323,323
BEGIN DESCRIPTION:
Mapping XS 96d19d6e
END DESCRIPTION:
XS GIS Cut Line= 3
      1637236.37      6999991.73      1637555.78      6999778.22
      1637988.11      6999554.24
#Sta/Elev= 30
  4615.2 1535.95  4832.5 1536.16  4850.0 1534.61  4883.5 1529.82  4898.5 1524.02
  4940.6 1515.97  4949.6 1512.87  4955.6 1512.11  4970.6 1505.68  4976.6 1505.43
  4985.6 1502.17  4991.6 1502.17  4995.9 1498.93  5001.8 1498.93  5004.9 1497.64
  5005.3 1497.14  5009.9 1497.64  5039.3 1498.26  5079.5 1498.26  5096.0 1505.48
  5101.6 1505.76  5118.1 1512.63  5220.5 1525.09  5250.9 1528.69  5273.0 1533.95
  5285.0 1535.01  5370.2 1539.92  5398.2 1540.31  5446.0 1541.10  5486.3 1541.63
#Mann=9,-1,0
  4615.2   0.035       0  4850.0    0.07       0  5004.9    0.07       0
  5009.9    0.07       0  5039.3    0.16       0  5220.5    0.07       0
  5285.0    0.16       0  5398.2    0.07       0  5446.0   0.035       0
Bank Sta=5004.9,5009.9
Exp/Cntr=0.3,0.1

Type RM Length L Ch R = 1,931,264,264,264
BEGIN DESCRIPTION:
Mapping XS 3a00a25d
END DESCRIPTION:
XS GIS Cut Line= 3
      1637419.34      7000280.72      1637744.84      7000030.74
      1638071.47      6999811.69
#Sta/Elev= 30
  4587.5 1537.99  4663.8 1536.67  4729.3 1535.38  4779.1 1531.66  4799.9 1526.45
  4814.4 1524.32  4907.8 1515.39  4943.2 1508.51  4957.7 1502.99  4974.5 1491.88
  4976.0 1490.73  4976.4 1490.23  4981.0 1490.73  4993.0 1490.95  4996.1 1492.49
  5022.2 1494.47  5044.0 1499.76  5050.0 1503.19  5086.0 1510.35  5101.0 1510.44
  5107.0 1512.05  5116.0 1511.63  5122.0 1513.76  5127.2 1513.63  5137.0 1514.09
  5173.0 1520.42  5260.1 1527.21  5287.1 1533.40  5302.1 1535.51  5391.2 1538.07
#Mann=6,-1,0
  4587.5   0.035       0  4663.8    0.07       0  4974.5    0.16       0
  4976.0    0.07       0  4981.0    0.16       0  5127.2    0.07       0
Bank Sta=4976,4981
Exp/Cntr=0.3,0.1

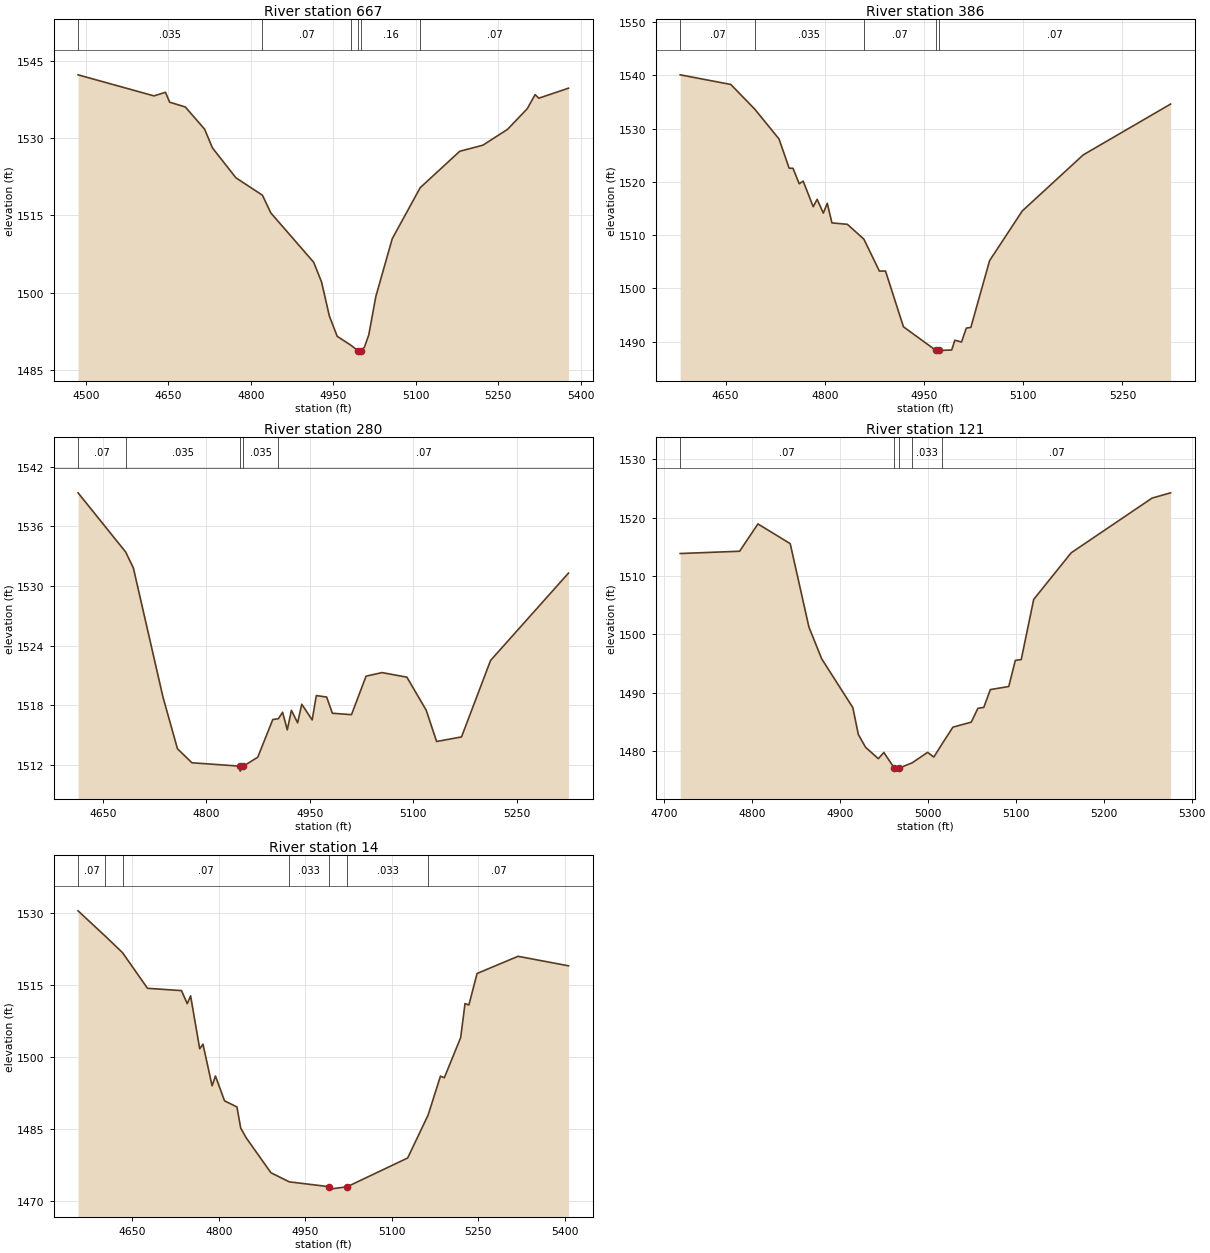
Type RM Length L Ch R = 1,667,281,281,281
BEGIN DESCRIPTION:
Mapping XS 18c2810f
END DESCRIPTION:
XS GIS Cut Line= 3
      1637547.35      7000555.05      1637931.47      7000216.50
      1638245.20      7000003.01
#Sta/Elev= 30
  4486.1 1542.37  4624.1 1538.27  4645.0 1538.97  4652.6 1537.04  4681.0 1536.12
  4716.1 1531.80  4730.4 1528.14  4773.1 1522.32  4821.2 1518.94  4836.6 1515.48
  4914.4 1505.89  4928.7 1502.05  4942.9 1495.43  4957.1 1491.48  4981.6 1489.77
  4994.6 1488.70  4995.0 1488.20  4999.7 1488.70  5006.4 1489.30  5014.5 1491.73
  5027.4 1499.23  5057.2 1510.47  5108.0 1520.40  5179.9 1527.49  5221.9 1528.67
  5266.7 1531.75  5302.6 1535.77  5316.9 1538.52  5323.6 1537.82  5377.6 1539.77
#Mann=6,-1,0
  4486.1   0.035       0  4821.2    0.07       0  4981.6    0.16       0
  4994.6    0.07       0  4999.7    0.16       0  5108.0    0.07       0
Bank Sta=4994.6,4999.7
Exp/Cntr=0.3,0.1

Type RM Length L Ch R = 1,386,106,106,106
BEGIN DESCRIPTION:
Mapping XS cc64ea73
END DESCRIPTION:
XS GIS Cut Line= 3
      1637711.21      7000671.36      1638063.85      7000447.84
      1638298.24      7000224.30
#Sta/Elev= 30
  4581.5 1540.11  4658.0 1538.30  4694.3 1533.65  4730.9 1528.06  4746.2 1522.57
  4752.1 1522.54  4761.4 1519.64  4767.4 1520.14  4782.6 1515.33  4788.5 1516.72
  4797.9 1514.12  4803.8 1515.97  4810.9 1512.29  4834.3 1512.02  4859.2 1509.23
  4882.6 1503.24  4891.9 1503.24  4919.0 1492.77  4968.2 1488.32  4968.6 1487.82
  4973.3 1488.32  4991.9 1488.41  4996.7 1490.24  5006.8 1489.91  5014.0 1492.52
  5020.9 1492.66  5049.2 1505.19  5098.6 1514.53  5190.8 1525.07  5322.9 1534.62
#Mann=5,-1,0
  4581.5    0.07       0  4694.3   0.035       0  4859.2    0.07       0
  4968.2    0.07       0  4973.3    0.07       0
Bank Sta=4968.2,4973.3
Exp/Cntr=0.3,0.1

Type RM Length L Ch R = 1,280,159,159,159
BEGIN DESCRIPTION:
Mapping XS 410ff9be
END DESCRIPTION:
XS GIS Cut Line= 3
      1637788.26      7000751.65      1638107.25      7000538.98
      1638380.34      7000358.01
#Sta/Elev= 30
  4613.9 1539.38  4682.9 1533.43  4694.1 1531.82  4736.9 1518.87  4758.0 1513.64
  4779.0 1512.23  4848.5 1511.89  4848.9 1511.39  4853.6 1511.89  4874.4 1512.79
  4896.2 1516.58  4904.3 1516.66  4910.4 1517.31  4917.2 1515.54  4923.2 1517.50
  4932.2 1516.25  4938.2 1518.12  4953.3 1516.54  4959.3 1518.99  4974.3 1518.84
  4982.6 1517.21  5010.3 1517.07  5031.4 1520.94  5054.6 1521.30  5090.6 1520.84
  5118.6 1517.52  5133.7 1514.37  5169.8 1514.83  5211.9 1522.52  5324.9 1531.31
#Mann=5,-1,0
  4613.9    0.07       0  4682.9   0.035       0  4848.5    0.07       0
  4853.6   0.035       0  4904.3    0.07       0
Bank Sta=4848.5,4853.6
Exp/Cntr=0.3,0.1

Type RM Length L Ch R = 1,121,107,107,107
BEGIN DESCRIPTION:
Mapping XS 8f614ba0
END DESCRIPTION:
XS GIS Cut Line= 3
      1637995.73      7000823.61      1638219.67      7000651.75
      1638403.72      7000446.86
#Sta/Elev= 30
  4718.4 1513.84  4786.0 1514.23  4806.8 1518.90  4843.5 1515.53  4864.8 1501.25
  4879.3 1495.83  4914.7 1487.49  4921.0 1482.88  4929.2 1480.70  4943.7 1478.75
  4950.0 1479.81  4962.0 1477.12  4962.3 1476.62  4967.1 1477.12  4982.2 1478.04
  4999.7 1479.83  5006.8 1479.03  5016.4 1481.32  5028.5 1484.14  5049.4 1485.00
  5056.9 1487.36  5063.6 1487.52  5071.1 1490.57  5092.0 1491.09  5099.5 1495.56
  5106.2 1495.70  5120.4 1506.00  5163.0 1513.96  5255.0 1523.32  5276.1 1524.22
#Mann=5,-1,0
  4718.4    0.07       0  4962.0   0.033       0  4967.1    0.07       0
  4982.2   0.033       0  5016.4    0.07       0
Bank Sta=4962,4967.1
Exp/Cntr=0.3,0.1

Type RM Length L Ch R = 1,14,0,0,0
BEGIN DESCRIPTION:
Chimney Creek 1155 1.0
END DESCRIPTION:
XS GIS Cut Line= 3
      1637910.64      7000950.36      1638295.42      7000728.42
      1638565.16      7000424.31
#Sta/Elev= 30
  4555.8 1530.50  4602.6 1525.27  4632.9 1521.78  4676.3 1514.35  4735.2 1513.87
  4745.2 1511.14  4751.0 1512.78  4766.8 1501.75  4772.5 1502.70  4788.3 1494.02
  4794.1 1496.07  4809.9 1490.89  4831.4 1489.62  4837.9 1485.23  4847.2 1483.23
  4890.3 1475.91  4922.1 1474.01  4991.6 1472.99  4992.1 1472.49  5022.6 1472.99
  5127.5 1478.98  5163.0 1487.93  5184.4 1496.04  5191.1 1495.71  5219.5 1504.09
  5227.0 1511.17  5233.7 1510.87  5247.9 1517.44  5319.0 1521.02  5406.5 1519.04
#Mann=7,-1,0
  4555.8    0.07       0  4602.6   0.035       0  4632.9    0.07       0
  4922.1   0.033       0  4991.6   0.033       0  5022.6   0.033       0
  5163.0    0.07       0
Bank Sta=4991.6,5022.6
Exp/Cntr=0.3,0.1

Chan Stop Cuts=-1