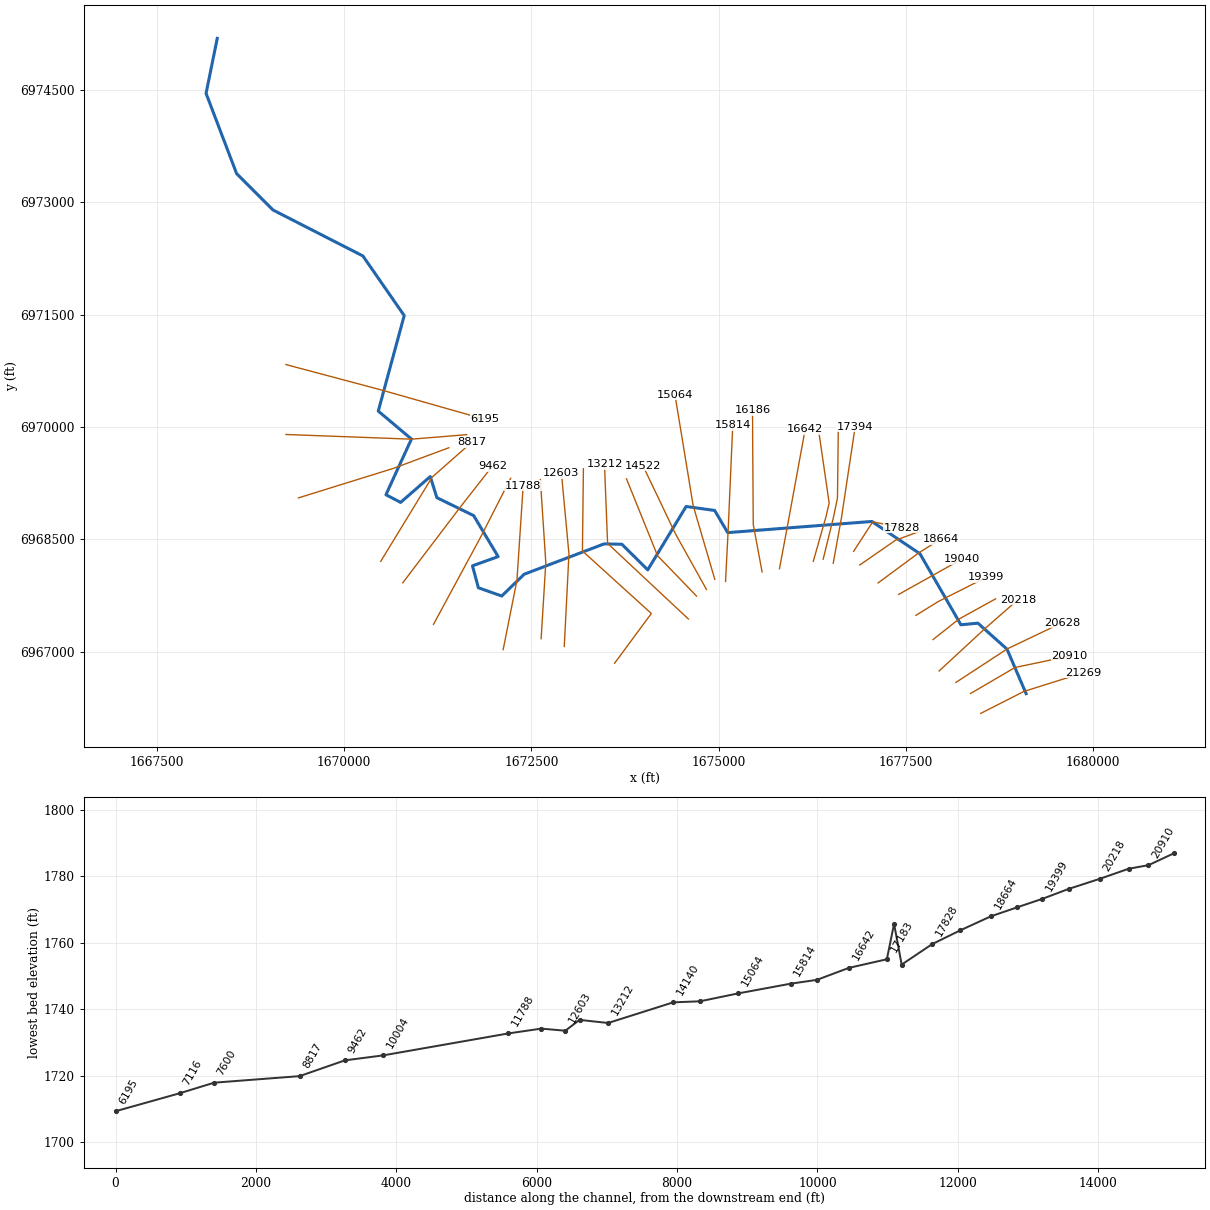
--- Chimney Creek 1156.prj (project) ---

Proj Title=Chimney Creek 1156 Base Level Engineering
Current Plan=p01
Default Exp/Contr=0.3,0.1
English Units
Geom File=g01
Flow File=f01
Plan File=p01
BEGIN DESCRIPTION:
Chimney Creek 1156
END DESCRIPTION:

--- Chimney Creek 1156.p01 (plan) ---

Plan Title=Multiple Run
Short Identifier=Multiple
Geom File=g01
Flow File=f01
Subcritical Flow
K Sum by GR= 0
Std Step Tol= 0.01
Critical Tol= 0.01
Num of Std Step Trials= 20
Max Error Tol= 0.3
Flow Tol Ratio= 0.001
Split Flow NTrial= 30
Split Flow Tol= 0.02
Split Flow Ratio= 0.02
Log Output Level= 0
Friction Slope Method= 1
Unsteady Friction Slope Method= 2
Unsteady Bridges Friction Slope Method= 1
Parabolic Critical Depth
Global Vel Dist=  1 , 1 , 1
Global Log Level= 0
CheckData=True
Encroach Param= -1, 0, 0, 0
BEGIN DESCRIPTION:
Multiple Run
END DESCRIPTION:

--- Chimney Creek 1156.f01 (steady flow) ---

Flow Title=Multiple
Number of Profiles=7
Profile Names=10-year,25-year,50-year,1pct_min,100-year,1pct_plu,500-year
River Rch & RM= Chimney Creek 11,Reach-1,21269
     234     320     390     237     473     944     704
River Rch & RM= Chimney Creek 11,Reach-1,20628
     276     382     468     286     572    1141     861
River Rch & RM= Chimney Creek 11,Reach-1,17394
     521     743     932     581    1159    2313    1817
River Rch & RM= Chimney Creek 11,Reach-1,12603
     694    1004    1271     799    1594    3180    2540
River Rch & RM= Chimney Creek 11,Reach-1,13
    1150    1699    2180    1386    2766    5519    4516
Boundary for River Rch & Prof#=Chimney Creek 11,Reach-1,1
Up Type=0
Dn Type=3
Dn Slope=0.005
Boundary for River Rch & Prof#=Chimney Creek 11,Reach-1,2
Up Type=0
Dn Type=3
Dn Slope=0.005
Boundary for River Rch & Prof#=Chimney Creek 11,Reach-1,3
Up Type=0
Dn Type=3
Dn Slope=0.005
Boundary for River Rch & Prof#=Chimney Creek 11,Reach-1,4
Up Type=0
Dn Type=3
Dn Slope=0.005
Boundary for River Rch & Prof#=Chimney Creek 11,Reach-1,5
Up Type=0
Dn Type=3
Dn Slope=0.005
Boundary for River Rch & Prof#=Chimney Creek 11,Reach-1,6
Up Type=0
Dn Type=3
Dn Slope=0.005
Boundary for River Rch & Prof#=Chimney Creek 11,Reach-1,7
Up Type=0
Dn Type=3
Dn Slope=0.005

--- Chimney Creek 1156.g01 (geometry) ---

Geom Title=Existing Conditions

River Reach=Chimney Creek 11,Reach-1
Reach XY= 30
      1679105.00      6966438.00      1678849.74      6967032.53
      1678461.74      6967378.87      1678234.45      6967357.44
      1677688.55      6968305.15      1677045.51      6968737.03
      1675120.39      6968588.08      1674946.45      6968884.18
      1674565.26      6968937.02      1674053.00      6968090.94
      1673707.45      6968432.54      1673470.16      6968437.62
      1672402.70      6968032.17      1672103.53      6967741.53
      1671791.76      6967851.62      1671712.67      6968144.52
      1672055.22      6968267.94      1671728.86      6968814.93
      1671237.86      6969054.45      1671148.81      6969336.58
      1670753.41      6968991.67      1670557.04      6969093.85
      1670897.92      6969838.00      1670454.80      6970210.64
      1670801.25      6971486.45      1670249.38      6972282.38
      1669048.94      6972896.14      1668563.14      6973381.94
      1668155.52      6974453.22      1668305.00      6975188.00

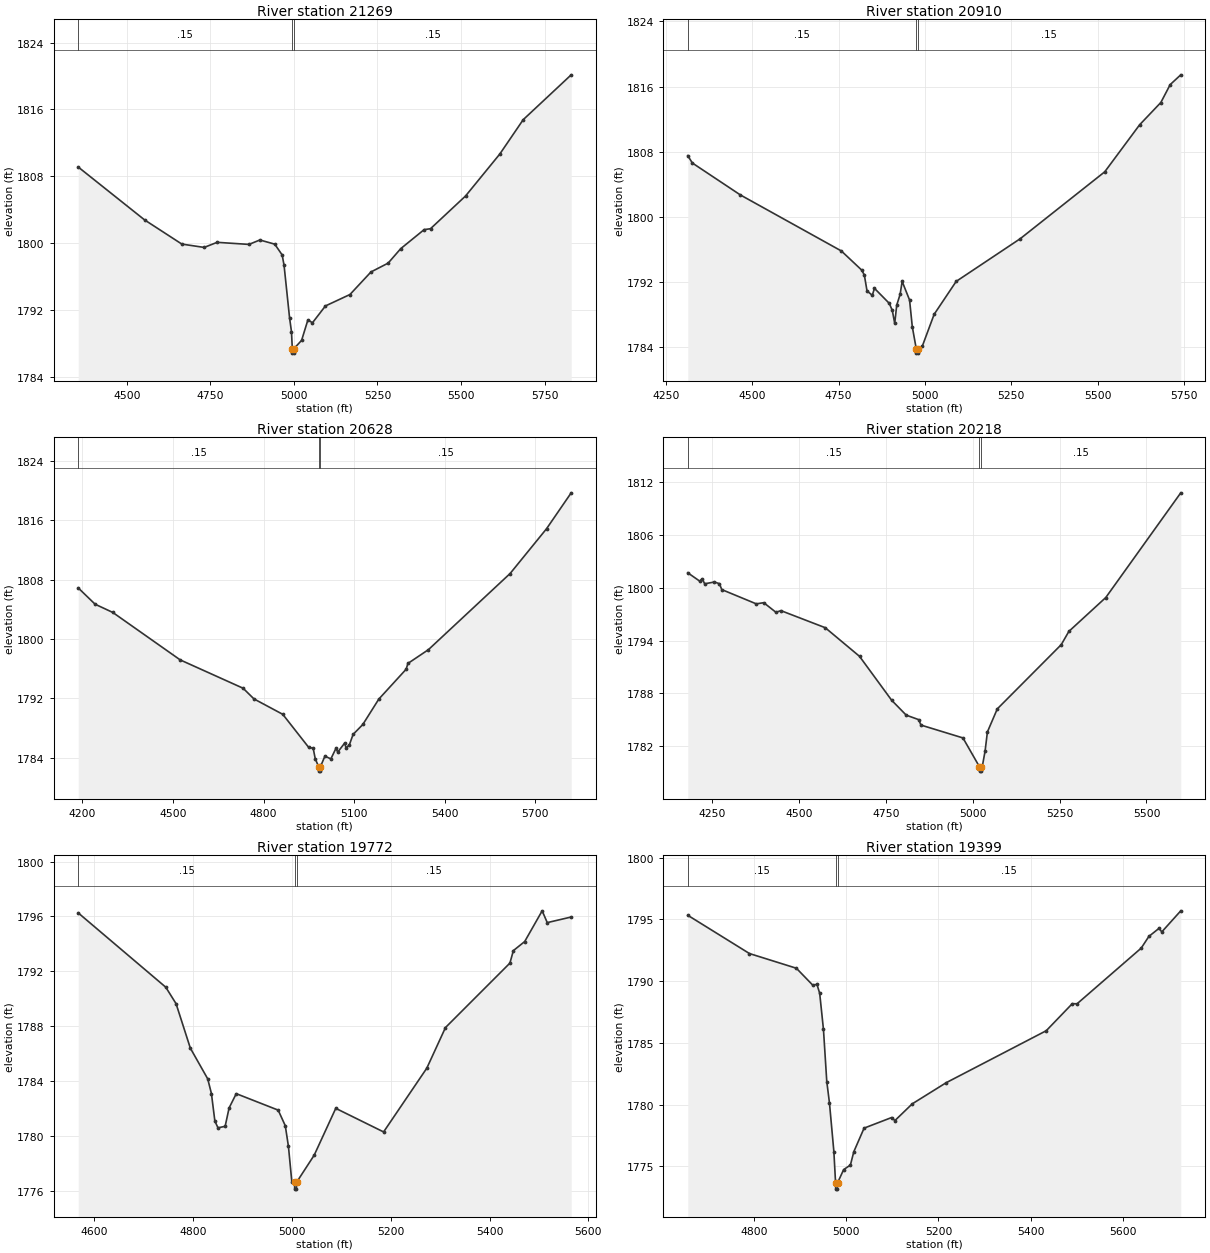
Type RM Length L Ch R = 1,21269,359,359,359
BEGIN DESCRIPTION:
Chimney Creek 1156 40.0
END DESCRIPTION:
XS GIS Cut Line= 3
      1678499.42      6966174.51      1679075.14      6966467.08
      1679866.66      6966716.20
#Sta/Elev= 30
  4354.2 1809.10  4553.1 1802.76  4664.4 1799.87  4731.2 1799.47  4770.1 1800.08
  4865.2 1799.83  4898.0 1800.36  4942.5 1799.86  4964.7 1798.57  4970.4 1797.32
  4987.0 1790.98  4992.6 1789.38  4995.1 1787.31  4995.4 1786.81  4998.9 1786.81
  4999.1 1787.31  5022.9 1788.34  5041.8 1790.80  5055.3 1790.44  5094.2 1792.46
  5167.6 1793.83  5230.5 1796.53  5281.9 1797.59  5319.5 1799.32  5389.6 1801.60
  5408.7 1801.71  5513.6 1805.63  5616.2 1810.66  5686.2 1814.77  5829.8 1820.14
#Mann=3,-1,0
  4354.2    0.15       0  4995.1    0.05       0  4999.1    0.15       0
Bank Sta=4995.1,4999.1
Exp/Cntr=0.3,0.1

Type RM Length L Ch R = 1,20910,282,282,282
BEGIN DESCRIPTION:
Mapping XS 017dfd38
END DESCRIPTION:
XS GIS Cut Line= 3
      1678363.51      6966440.16      1678958.12      6966787.38
      1679681.44      6966938.97
#Sta/Elev= 30
  4313.2 1807.53  4326.5 1806.62  4465.5 1802.70  4757.9 1795.82  4816.6 1793.48
  4824.5 1792.87  4832.3 1790.91  4847.6 1790.37  4853.8 1791.23  4896.8 1789.38
  4905.5 1788.51  4912.5 1786.92  4918.3 1789.16  4928.2 1790.50  4934.0 1792.08
  4955.5 1789.79  4963.4 1786.51  4975.0 1783.77  4975.3 1783.27  4978.8 1783.27
  4979.0 1783.77  4992.7 1784.16  5026.7 1788.04  5090.5 1792.08  5276.2 1797.33
  5520.7 1805.54  5621.8 1811.32  5683.1 1814.05  5710.2 1816.25  5740.8 1817.45
#Mann=3,-1,0
  4313.2    0.15       0  4975.0    0.05       0  4979.0    0.15       0
Bank Sta=4975,4979
Exp/Cntr=0.3,0.1

Type RM Length L Ch R = 1,20628,410,410,410
BEGIN DESCRIPTION:
Mapping XS 9a6210b4
END DESCRIPTION:
XS GIS Cut Line= 3
      1678168.15      6966587.70      1678851.78      6967034.77
      1679587.46      6967386.33
#Sta/Elev= 30
  4186.4 1806.91  4242.4 1804.71  4300.9 1803.60  4524.1 1797.20  4732.3 1793.38
  4768.3 1791.94  4863.7 1789.86  4949.2 1785.42  4964.4 1785.28  4971.2 1783.87
  4983.4 1782.70  4983.7 1782.20  4987.2 1782.20  4987.4 1782.70  5003.2 1784.22
  5022.9 1783.85  5040.0 1785.29  5045.6 1784.76  5068.2 1785.96  5073.8 1785.32
  5084.4 1785.77  5096.5 1787.15  5128.7 1788.49  5181.6 1791.91  5272.3 1795.95
  5277.9 1796.72  5345.9 1798.58  5616.4 1808.85  5737.0 1814.89  5818.6 1819.73
#Mann=3,-1,0
  4186.4    0.15       0  4983.4    0.05       0  4987.4    0.15       0
Bank Sta=4983.4,4987.4
Exp/Cntr=0.3,0.1

Type RM Length L Ch R = 1,20218,446,446,446
BEGIN DESCRIPTION:
Mapping XS c0bce261
END DESCRIPTION:
XS GIS Cut Line= 3
      1677943.65      6966740.64      1678547.83      6967299.69
      1678995.74      6967692.04
#Sta/Elev= 30
  4180.0 1801.71  4214.4 1800.76  4221.8 1801.03  4228.6 1800.46  4256.9 1800.66
  4271.1 1800.47  4277.9 1799.80  4377.1 1798.18  4398.7 1798.31  4433.8 1797.22
  4448.0 1797.41  4575.6 1795.47  4674.2 1792.22  4766.7 1787.23  4808.6 1785.54
  4844.3 1785.03  4851.1 1784.41  4971.9 1782.95  5019.3 1779.68  5019.6 1779.18
  5023.1 1779.18  5023.4 1779.68  5028.0 1779.81  5035.6 1781.47  5042.2 1783.63
  5070.7 1786.25  5254.8 1793.55  5276.6 1795.05  5382.9 1798.90  5598.6 1810.79
#Mann=3,-1,0
  4180.0    0.15       0  5019.3    0.05       0  5023.4    0.15       0
Bank Sta=5019.3,5023.4
Exp/Cntr=0.3,0.1

Type RM Length L Ch R = 1,19772,373,373,373
BEGIN DESCRIPTION:
Mapping XS 19b8a6f4
END DESCRIPTION:
XS GIS Cut Line= 3
      1677863.49      6967160.82      1678205.47      6967431.63
      1678697.48      6967703.62
#Sta/Elev= 30
  4567.0 1796.26  4744.4 1790.84  4765.2 1789.64  4794.1 1786.40  4829.3 1784.16
  4836.8 1783.09  4843.8 1781.08  4850.1 1780.59  4864.6 1780.70  4872.6 1782.04
  4887.1 1783.08  4972.0 1781.88  4986.4 1780.74  4992.8 1779.23  4999.7 1776.63
  5005.2 1776.62  5005.4 1776.12  5009.0 1776.12  5009.3 1776.62  5045.0 1778.60
  5088.6 1782.01  5185.5 1780.29  5273.0 1784.94  5310.8 1787.90  5441.3 1792.60
  5448.3 1793.51  5471.2 1794.17  5506.6 1796.41  5516.9 1795.55  5565.4 1795.96
#Mann=3,-1,0
  4567.0    0.15       0  5005.2    0.05       0  5009.3    0.15       0
Bank Sta=5005.2,5009.3
Exp/Cntr=0.3,0.1

Type RM Length L Ch R = 1,19399,359,359,359
BEGIN DESCRIPTION:
Mapping XS bc4c4fe0
END DESCRIPTION:
XS GIS Cut Line= 3
      1677634.26      6967483.70      1677929.43      6967666.01
      1678575.31      6967992.42
#Sta/Elev= 30
  4655.5 1795.33  4789.5 1792.23  4891.4 1791.04  4926.7 1789.68  4936.1 1789.73
  4942.0 1789.01  4950.2 1786.08  4957.4 1781.86  4963.2 1780.14  4972.8 1776.19
  4976.5 1773.65  4976.8 1773.15  4980.5 1773.15  4980.7 1773.65  4994.0 1774.73
  5008.7 1775.10  5016.1 1776.18  5038.4 1778.09  5098.3 1778.95  5105.3 1778.70
  5143.1 1780.06  5216.7 1781.77  5434.0 1785.98  5490.5 1788.17  5500.9 1788.16
  5640.2 1792.67  5656.9 1793.62  5679.2 1794.28  5684.8 1793.98  5726.1 1795.69
#Mann=3,-1,0
  4655.5    0.15       0  4976.5    0.05       0  4980.7    0.15       0
Bank Sta=4976.5,4980.7
Exp/Cntr=0.3,0.1

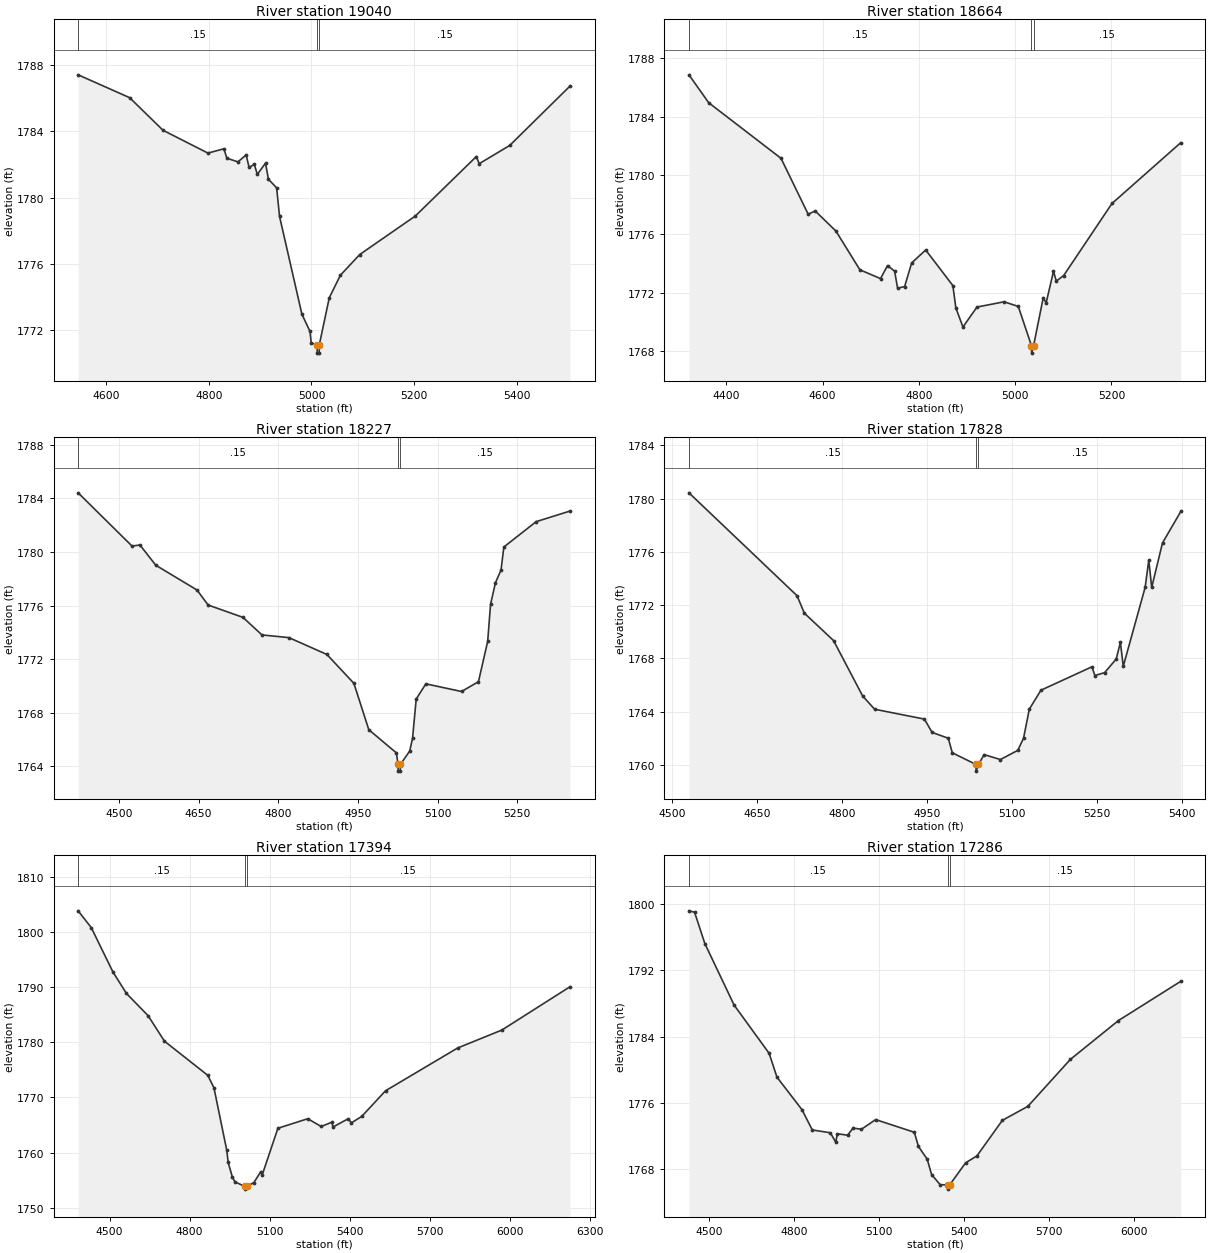
Type RM Length L Ch R = 1,19040,376,376,376
BEGIN DESCRIPTION:
Mapping XS 32301c07
END DESCRIPTION:
XS GIS Cut Line= 3
      1677404.04      6967763.09      1677801.65      6967985.34
      1678241.30      6968231.13
#Sta/Elev= 30
  4545.0 1787.42  4645.4 1786.04  4710.5 1784.07  4798.1 1782.69  4829.3 1782.95
  4835.0 1782.38  4856.7 1782.16  4872.7 1782.58  4878.4 1781.82  4888.6 1782.01
  4894.4 1781.40  4910.4 1782.08  4916.1 1781.11  4932.1 1780.59  4937.8 1778.86
  4981.4 1772.95  4997.2 1771.91  4999.6 1771.22  5011.0 1771.10  5011.3 1770.60
  5015.0 1770.60  5015.3 1771.10  5034.8 1773.95  5056.5 1775.31  5094.2 1776.56
  5202.7 1778.89  5321.5 1782.48  5327.2 1782.05  5386.6 1783.15  5504.2 1786.74
#Mann=3,-1,0
  4545.0    0.15       0  5011.0    0.05       0  5015.3    0.15       0
Bank Sta=5011,5015.3
Exp/Cntr=0.3,0.1

Type RM Length L Ch R = 1,18664,437,437,437
BEGIN DESCRIPTION:
Mapping XS 9bed1265
END DESCRIPTION:
XS GIS Cut Line= 3
      1677129.45      6967916.95      1677674.57      6968319.71
      1677966.22      6968501.99
#Sta/Elev= 30
  4322.4 1786.85  4363.3 1784.95  4513.6 1781.16  4570.0 1777.35  4584.6 1777.57
  4627.7 1776.20  4677.4 1773.56  4720.3 1772.96  4734.9 1773.85  4749.6 1773.47
  4755.8 1772.30  4770.4 1772.42  4785.0 1774.03  4814.2 1774.91  4870.6 1772.48
  4876.8 1770.96  4891.5 1769.66  4920.7 1771.02  4977.1 1771.38  5006.5 1771.06
  5033.9 1768.38  5034.2 1767.88  5038.2 1768.38  5058.4 1771.67  5064.3 1771.30
  5079.6 1773.45  5085.5 1772.79  5100.8 1773.17  5201.1 1778.08  5344.1 1782.23
#Mann=3,-1,0
  4322.4    0.15       0  5033.9    0.05       0  5038.2    0.15       0
Bank Sta=5033.9,5038.2
Exp/Cntr=0.3,0.1

Type RM Length L Ch R = 1,18227,399,399,399
BEGIN DESCRIPTION:
Mapping XS 8cc013f7
END DESCRIPTION:
XS GIS Cut Line= 3
      1676884.66      6968156.53      1677362.07      6968486.38
      1677686.70      6968606.16
#Sta/Elev= 30
  4423.2 1784.41  4524.7 1780.44  4539.6 1780.52  4569.4 1779.01  4647.1 1777.16
  4668.0 1776.04  4733.6 1775.12  4769.4 1773.81  4820.1 1773.61  4891.8 1772.35
  4942.5 1770.20  4970.6 1766.74  5022.6 1765.01  5025.7 1764.15  5026.0 1763.65
  5029.8 1763.65  5030.1 1764.15  5047.7 1765.15  5053.0 1766.10  5059.9 1769.03
  5078.1 1770.16  5145.2 1769.59  5177.1 1770.32  5194.5 1773.33  5199.9 1776.09
  5209.1 1777.70  5219.6 1778.65  5225.0 1780.37  5285.8 1782.26  5349.5 1783.05
#Mann=3,-1,0
  4423.2    0.15       0  5025.7    0.05       0  5030.1    0.15       0
Bank Sta=5025.7,5030.1
Exp/Cntr=0.3,0.1

Type RM Length L Ch R = 1,17828,434,434,434
BEGIN DESCRIPTION:
Chimney Creek 1156 34.0
END DESCRIPTION:
XS GIS Cut Line= 3
      1676802.11      6968337.98      1677057.50      6968732.65
      1677446.58      6968651.75
#Sta/Elev= 30
  4529.9 1780.43  4720.5 1772.70  4733.4 1771.39  4784.9 1769.33  4836.3 1765.16
  4857.4 1764.17  4945.1 1763.43  4958.7 1762.43  4987.3 1761.99  4994.3 1760.90
  5036.1 1760.02  5036.4 1759.52  5040.5 1760.02  5050.5 1760.76  5079.2 1760.39
  5109.8 1761.08  5120.0 1761.99  5130.2 1764.18  5150.7 1765.60  5240.7 1767.36
  5245.8 1766.70  5263.0 1766.92  5283.4 1767.94  5290.8 1769.19  5295.9 1767.40
  5334.5 1773.33  5340.9 1775.38  5346.0 1773.32  5365.1 1776.67  5397.4 1779.03
#Mann=3,-1,0
  4529.9    0.15       0  5036.1    0.05       0  5040.5    0.15       0
Bank Sta=5036.1,5040.5
Exp/Cntr=0.3,0.1

Type RM Length L Ch R = 1,17394,108,108,108
BEGIN DESCRIPTION:
Chimney Creek 1156 33.0
END DESCRIPTION:
XS GIS Cut Line= 3
      1676529.56      6968179.59      1676639.78      6968787.48
      1676822.54      6970000.39
#Sta/Elev= 30
  4382.2 1803.85  4431.4 1800.81  4512.7 1792.76  4563.5 1788.86  4644.8 1784.82
  4705.8 1780.21  4868.4 1774.01  4891.5 1771.75  4939.6 1760.40  4944.9 1758.21
  4959.9 1755.66  4970.0 1754.69  5007.0 1753.87  5007.5 1753.37  5014.3 1753.87
  5041.0 1754.55  5067.4 1756.56  5072.5 1755.95  5131.3 1764.41  5243.2 1766.14
  5293.8 1764.73  5333.1 1765.50  5338.2 1764.65  5394.9 1766.13  5407.1 1765.40
  5445.5 1766.55  5534.9 1771.21  5805.7 1778.98  5971.4 1782.23  6226.6 1790.08
#Mann=3,-1,0
  4382.2    0.15       0  5007.0    0.05       0  5014.3    0.15       0
Bank Sta=5007,5014.3
Exp/Cntr=0.3,0.1

Type RM Length L Ch R = 1,17286,103,103,103
BEGIN DESCRIPTION:
Mapping XS e13bc9d1
END DESCRIPTION:
XS GIS Cut Line= 4
      1676395.45      6968233.02      1676534.34      6968798.99
      1676586.42      6969052.46      1676596.84      6969948.27
#Sta/Elev= 30
  4428.5 1799.20  4448.3 1799.03  4484.7 1795.24  4588.1 1787.82  4711.6 1782.01
  4739.3 1779.13  4827.6 1775.21  4864.1 1772.76  4927.9 1772.42  4947.2 1771.27
  4952.3 1772.30  4988.8 1772.13  5008.2 1772.99  5037.6 1772.84  5087.9 1774.01
  5224.6 1772.48  5239.0 1770.77  5270.0 1769.23  5285.6 1767.38  5315.6 1766.16
  5341.9 1766.12  5342.4 1765.62  5349.2 1766.12  5405.6 1768.79  5445.6 1769.63
  5535.6 1773.92  5625.6 1775.61  5775.6 1781.27  5945.6 1785.96  6165.9 1790.70
#Mann=3,-1,0
  4428.5    0.15       0  5341.9    0.05       0  5349.2    0.15       0
Bank Sta=5341.9,5349.2
Exp/Cntr=0.3,0.1

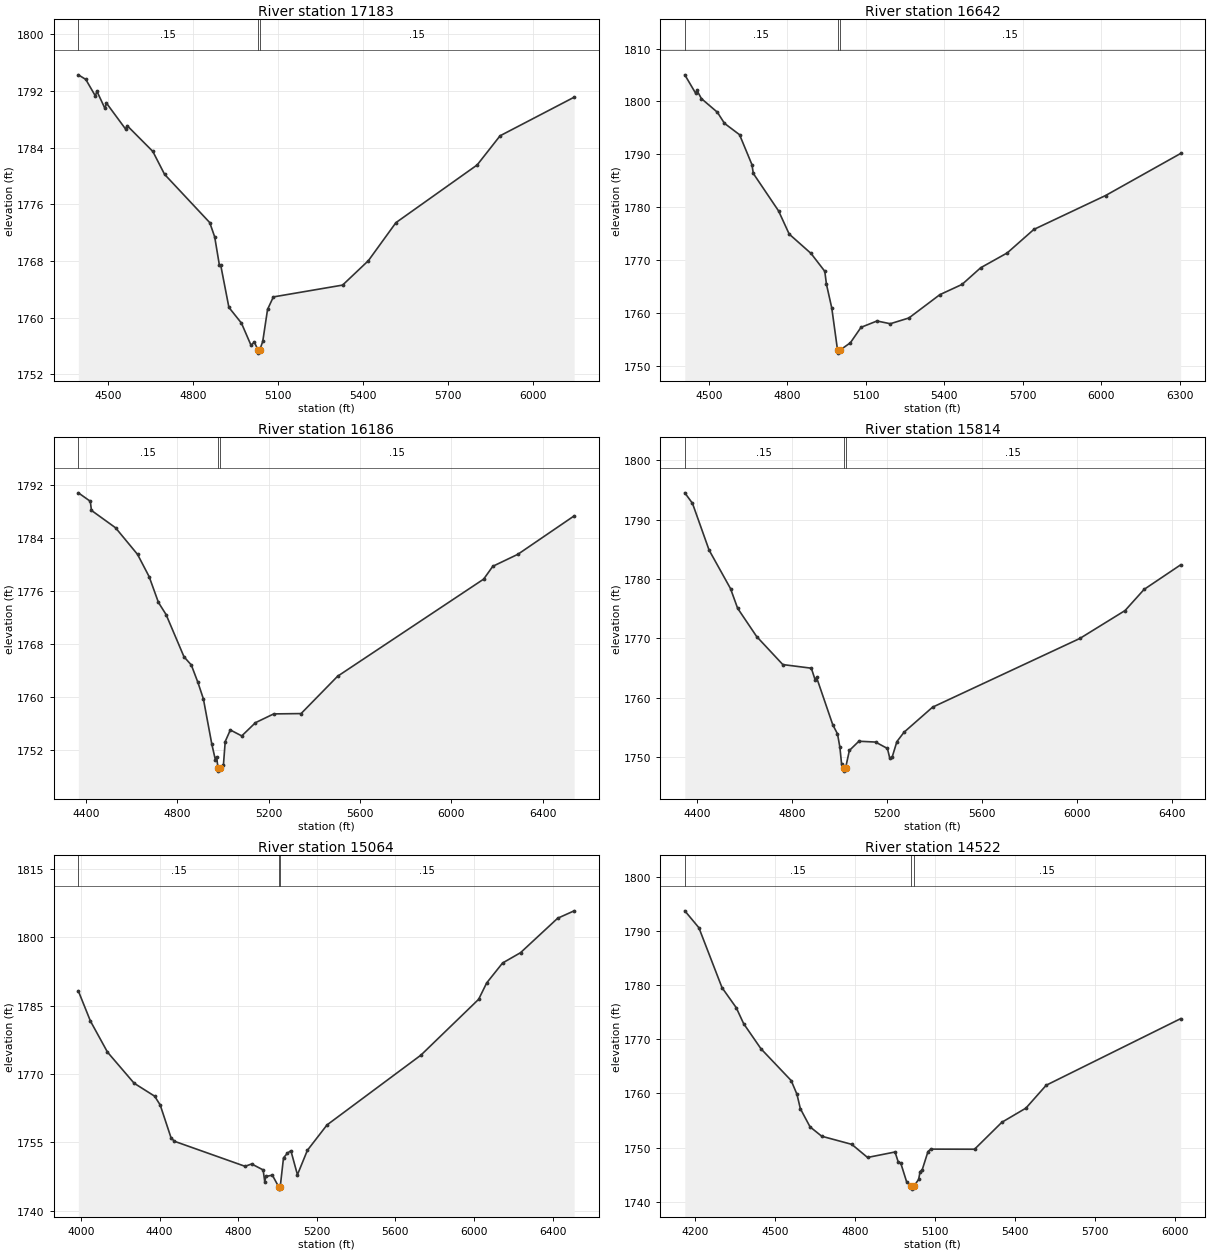
Type RM Length L Ch R = 1,17183,541,541,541
BEGIN DESCRIPTION:
Mapping XS 866995d9
END DESCRIPTION:
XS GIS Cut Line= 4
      1676263.50      6968205.21      1676433.65      6968802.46
      1676475.31      6968983.01      1676339.94      6969916.74
#Sta/Elev= 30
  4394.0 1794.28  4420.3 1793.63  4454.2 1791.29  4459.4 1791.97  4488.0 1789.53
  4493.2 1790.29  4560.9 1786.61  4566.1 1787.11  4656.9 1783.46  4698.4 1780.22
  4857.7 1773.41  4875.2 1771.39  4891.5 1767.47  4896.7 1767.35  4925.4 1761.43
  4969.6 1759.21  5003.4 1756.08  5015.0 1756.54  5027.3 1755.47  5027.8 1754.97
  5034.6 1755.47  5044.8 1756.62  5061.8 1761.15  5082.3 1762.91  5326.6 1764.58
  5417.6 1768.03  5514.8 1773.40  5801.5 1781.55  5882.4 1785.67  6143.8 1791.12
#Mann=3,-1,0
  4394.0    0.15       0  5027.3    0.05       0  5034.6    0.15       0
Bank Sta=5027.3,5034.6
Exp/Cntr=0.3,0.1

Type RM Length L Ch R = 1,16642,456,456,456
BEGIN DESCRIPTION:
Mapping XS b710aea5
END DESCRIPTION:
XS GIS Cut Line= 3
      1675811.77      6968105.57      1675922.88      6968699.33
      1676155.52      6969970.15
#Sta/Elev= 30
  4407.5 1805.03  4448.9 1801.55  4454.0 1802.08  4471.0 1800.53  4532.1 1797.95
  4559.2 1795.85  4616.9 1793.70  4664.3 1788.03  4669.5 1786.37  4766.0 1779.29
  4806.7 1774.90  4890.2 1771.24  4942.8 1767.86  4949.2 1765.40  4969.5 1760.92
  4991.8 1752.88  4992.3 1752.38  4999.1 1752.88  5040.7 1754.34  5081.4 1757.26
  5142.4 1758.46  5193.2 1757.94  5264.4 1759.03  5382.8 1763.44  5467.7 1765.38
  5538.9 1768.53  5640.5 1771.34  5742.2 1775.78  6016.7 1782.20  6303.5 1790.15
#Mann=3,-1,0
  4407.5    0.15       0  4991.8    0.05       0  4999.1    0.15       0
Bank Sta=4991.8,4999.1
Exp/Cntr=0.3,0.1

Type RM Length L Ch R = 1,16186,372,372,372
BEGIN DESCRIPTION:
Mapping XS d73e2b63
END DESCRIPTION:
XS GIS Cut Line= 3
      1675579.82      6968062.90      1675461.77      6968698.29
      1675451.37      6970224.49
#Sta/Elev= 30
  4365.8 1790.89  4418.2 1789.61  4423.3 1788.23  4528.9 1785.60  4625.3 1781.57
  4676.1 1778.20  4716.8 1774.30  4750.2 1772.47  4828.7 1766.08  4860.9 1764.83
  4889.7 1762.20  4913.7 1759.71  4950.7 1752.85  4966.5 1750.44  4971.6 1750.95
  4977.6 1749.27  4978.1 1748.77  4985.0 1749.27  5001.6 1749.71  5009.4 1753.25
  5031.8 1755.00  5081.8 1754.10  5141.8 1756.10  5221.8 1757.43  5341.8 1757.48
  5501.8 1763.13  6141.8 1777.83  6181.8 1779.77  6291.8 1781.59  6538.3 1787.40
#Mann=3,-1,0
  4365.8    0.15       0  4977.6    0.05       0  4985.0    0.15       0
Bank Sta=4977.6,4985
Exp/Cntr=0.3,0.1

Type RM Length L Ch R = 1,15814,750,750,750
BEGIN DESCRIPTION:
Mapping XS e01749e3
END DESCRIPTION:
XS GIS Cut Line= 3
      1675091.81      6967935.76      1675125.66      6968597.25
      1675188.16      6970021.72
#Sta/Elev= 30
  4347.2 1794.54  4379.5 1792.77  4449.6 1784.88  4539.7 1778.40  4569.7 1775.08
  4649.8 1770.32  4760.0 1765.59  4880.1 1764.98  4897.0 1762.91  4902.0 1763.44
  4970.3 1755.45  4990.3 1753.91  5000.3 1751.67  5007.4 1748.86  5016.5 1748.13
  5017.0 1747.63  5024.2 1748.13  5040.3 1751.11  5080.4 1752.67  5150.4 1752.53
  5200.5 1751.45  5210.5 1749.81  5220.5 1749.99  5240.5 1752.61  5270.6 1754.19
  5390.7 1758.41  6011.3 1770.00  6201.5 1774.70  6281.5 1778.26  6435.4 1782.40
#Mann=3,-1,0
  4347.2    0.15       0  5016.5    0.05       0  5024.2    0.15       0
Bank Sta=5016.5,5024.2
Exp/Cntr=0.3,0.1

Type RM Length L Ch R = 1,15064,542,542,542
BEGIN DESCRIPTION:
Mapping XS 5a98d62b
END DESCRIPTION:
XS GIS Cut Line= 3
      1674947.88      6967965.65      1674659.69      6968948.29
      1674416.64      6970427.42
#Sta/Elev= 30
  3986.6 1788.24  4048.3 1781.61  4134.9 1774.80  4270.4 1767.97  4374.9 1765.12
  4403.1 1763.19  4458.0 1756.03  4475.1 1755.22  4835.1 1749.71  4868.5 1750.23
  4927.0 1748.92  4935.3 1746.30  4940.5 1747.48  4973.9 1747.77  5006.2 1745.20
  5006.7 1744.70  5013.9 1745.20  5030.6 1751.57  5050.9 1752.61  5068.2 1753.14
  5101.5 1747.86  5152.2 1753.23  5251.9 1758.80  5729.9 1774.14  6023.7 1786.41
  6064.3 1789.99  6145.4 1794.38  6236.6 1796.64  6425.6 1804.21  6509.6 1805.84
#Mann=3,-1,0
  3986.6    0.15       0  5006.2    0.05       0  5013.9    0.15       0
Bank Sta=5006.2,5013.9
Exp/Cntr=0.3,0.1

Type RM Length L Ch R = 1,14522,382,382,382
BEGIN DESCRIPTION:
Mapping XS 1acf183e
END DESCRIPTION:
XS GIS Cut Line= 3
      1674837.19      6967829.57      1674425.75      6968566.52
      1673988.31      6969483.06
#Sta/Elev= 30
  4162.1 1793.74  4214.9 1790.62  4301.7 1779.55  4355.0 1775.85  4382.8 1772.90
  4447.9 1768.25  4561.0 1762.39  4582.7 1759.86  4595.5 1757.19  4631.9 1753.83
  4675.7 1752.10  4788.4 1750.60  4847.5 1748.18  4950.6 1749.19  4962.1 1747.42
  4972.3 1747.10  4994.0 1743.69  5012.3 1742.83  5012.8 1742.33  5020.4 1742.83
  5039.1 1744.11  5044.6 1745.57  5052.1 1745.84  5074.2 1749.27  5084.5 1749.72
  5248.8 1749.70  5351.3 1754.68  5441.4 1757.29  5517.5 1761.52  6021.7 1773.82
#Mann=3,-1,0
  4162.1    0.15       0  5012.3    0.05       0  5020.4    0.15       0
Bank Sta=5012.3,5020.4
Exp/Cntr=0.3,0.1

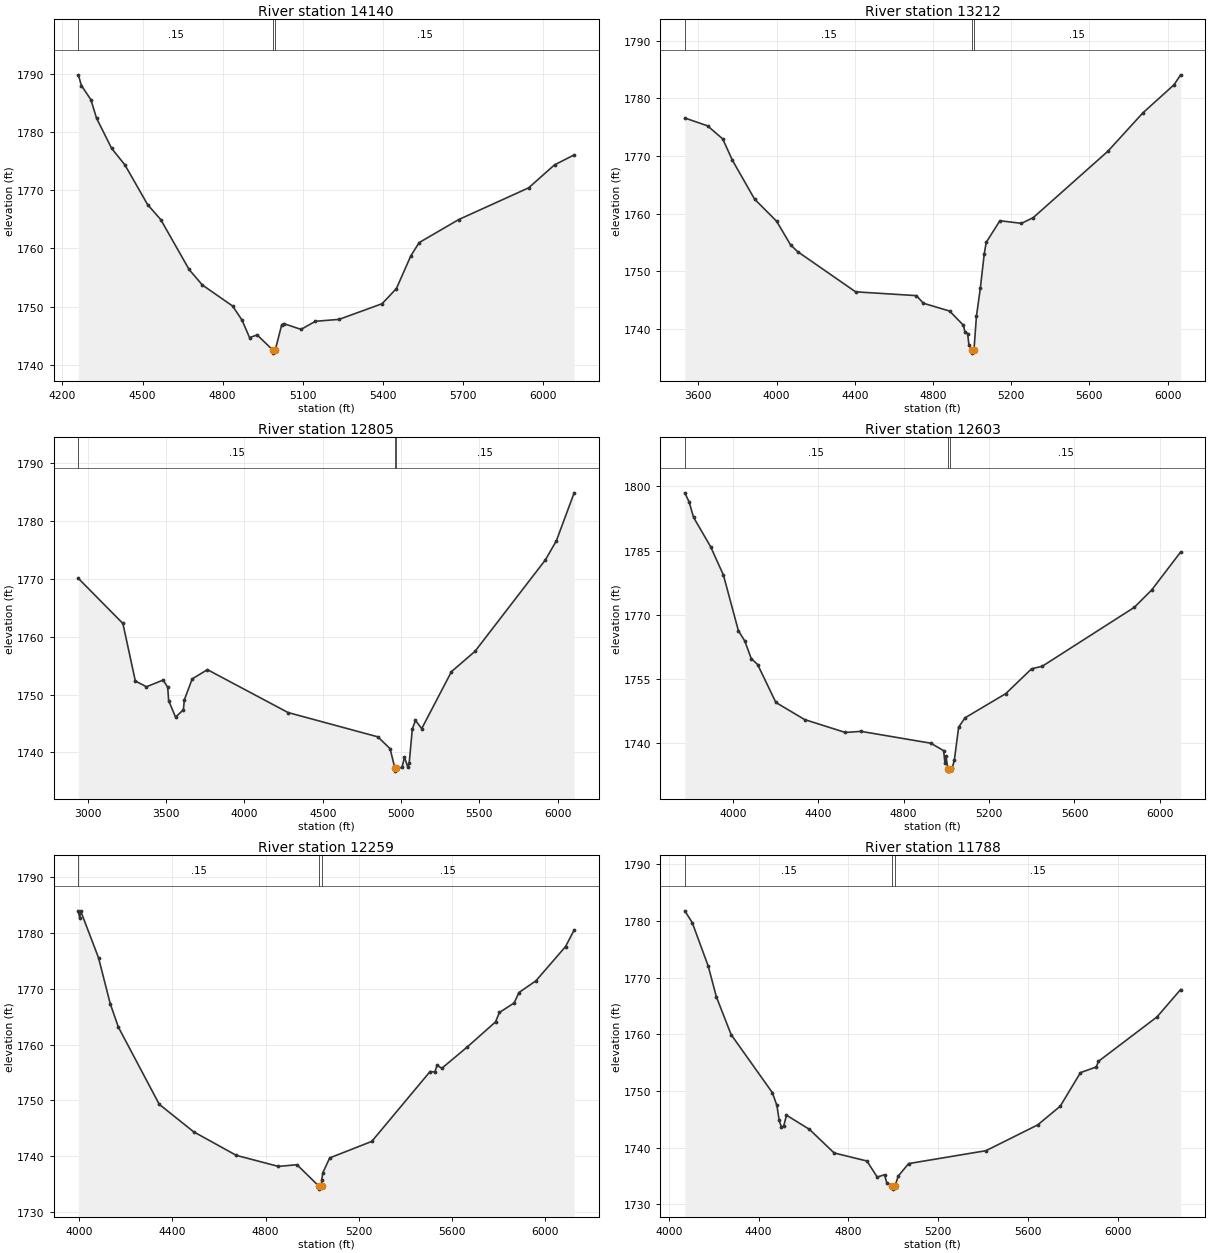
Type RM Length L Ch R = 1,14140,928,928,928
BEGIN DESCRIPTION:
Mapping XS 9a808790
END DESCRIPTION:
XS GIS Cut Line= 3
      1674704.37      6967741.02      1674183.56      6968280.06
      1673769.49      6969306.12
#Sta/Elev= 30
  4259.7 1789.83  4271.2 1787.99  4306.7 1785.56  4327.8 1782.39  4384.4 1777.19
  4434.0 1774.36  4518.9 1767.54  4568.3 1764.95  4674.3 1756.38  4723.9 1753.72
  4837.1 1750.11  4872.4 1747.69  4900.7 1744.67  4929.0 1745.14  4988.4 1742.51
  4988.9 1742.01  4996.6 1742.51  5021.0 1746.88  5028.6 1747.08  5093.3 1746.09
  5147.1 1747.48  5235.7 1747.81  5396.7 1750.50  5450.4 1753.11  5504.1 1758.71
  5535.4 1761.00  5683.9 1764.97  5945.2 1770.41  6042.2 1774.36  6115.7 1776.07
#Mann=3,-1,0
  4259.7    0.15       0  4988.4    0.05       0  4996.6    0.15       0
Bank Sta=4988.4,4996.6
Exp/Cntr=0.3,0.1

Type RM Length L Ch R = 1,13212,407,407,407
BEGIN DESCRIPTION:
Mapping XS b3b7d16a
END DESCRIPTION:
XS GIS Cut Line= 3
      1674595.90      6967434.58      1673516.89      6968444.12
      1673475.23      6969501.46
#Sta/Elev= 30
  3530.9 1776.61  3647.1 1775.25  3724.8 1772.98  3774.6 1769.26  3887.9 1762.52
  4000.8 1758.68  4071.6 1754.60  4107.3 1753.43  4404.3 1746.44  4715.4 1745.78
  4750.9 1744.46  4885.4 1743.10  4956.2 1740.62  4963.1 1739.55  4977.3 1739.19
  4984.1 1737.22  5001.4 1736.30  5001.9 1735.80  5009.7 1736.30  5022.4 1742.18
  5042.4 1747.09  5062.5 1753.06  5072.5 1755.03  5142.5 1758.78  5252.6 1758.32
  5312.7 1759.31  5694.7 1770.84  5873.1 1777.48  6033.2 1782.38  6066.7 1784.10
#Mann=3,-1,0
  3530.9    0.15       0  5001.4    0.05       0  5009.7    0.15       0
Bank Sta=5001.4,5009.7
Exp/Cntr=0.3,0.1

Type RM Length L Ch R = 1,12805,202,202,202
BEGIN DESCRIPTION:
Mapping XS 60bbfeee
END DESCRIPTION:
XS GIS Cut Line= 4
      1673610.70      6966844.33      1674101.13      6967508.35
      1673180.96      6968342.56      1673193.98      6969441.57
#Sta/Elev= 30
  2938.8 1770.10  3223.4 1762.29  3302.8 1752.34  3373.8 1751.34  3480.2 1752.50
  3509.5 1751.26  3515.7 1748.94  3559.6 1746.09  3609.7 1747.36  3615.9 1749.08
  3666.0 1752.70  3763.3 1754.30  4278.1 1746.88  4851.9 1742.67  4929.6 1740.63
  4960.6 1737.24  4961.1 1736.74  4968.9 1737.24  5006.3 1737.37  5021.8 1739.19
  5041.8 1737.48  5051.8 1738.12  5071.8 1744.02  5091.8 1745.51  5131.8 1744.10
  5321.8 1753.96  5471.8 1757.46  5921.8 1773.30  5991.8 1776.60  6105.4 1784.90
#Mann=3,-1,0
  2938.8    0.15       0  4960.6    0.05       0  4968.9    0.15       0
Bank Sta=4960.6,4968.9
Exp/Cntr=0.3,0.1

Type RM Length L Ch R = 1,12603,344,344,344
BEGIN DESCRIPTION:
Mapping XS ed4f3a8a
END DESCRIPTION:
XS GIS Cut Line= 3
      1672938.45      6967067.30      1673000.95      6968303.41
      1672900.27      6969383.13
#Sta/Elev= 30
  3775.1 1798.48  3795.8 1796.31  3815.9 1792.77  3896.0 1785.90  3956.0 1779.27
  4026.1 1766.28  4056.2 1763.86  4086.2 1759.77  4116.2 1758.38  4201.6 1749.52
  4336.5 1745.52  4526.8 1742.51  4599.9 1742.77  4927.3 1740.00  4987.4 1738.26
  4993.2 1735.44  4998.2 1736.99  5007.1 1733.98  5007.6 1733.48  5018.0 1733.98
  5027.7 1734.27  5037.5 1736.04  5057.6 1743.76  5087.7 1745.94  5278.5 1751.59
  5399.1 1757.38  5449.1 1757.97  5880.4 1771.74  5961.5 1775.78  6097.2 1784.65
#Mann=3,-1,0
  3775.1    0.15       0  5007.1    0.05       0  5018.0    0.15       0
Bank Sta=5007.1,5018
Exp/Cntr=0.3,0.1

Type RM Length L Ch R = 1,12259,471,471,471
BEGIN DESCRIPTION:
Mapping XS 8bb9460f
END DESCRIPTION:
XS GIS Cut Line= 3
      1672629.42      6967171.47      1672691.92      6968185.36
      1672619.12      6969294.76
#Sta/Elev= 30
  3996.2 1783.94  4001.7 1782.67  4006.7 1783.86  4082.9 1775.53  4133.0 1767.32
  4168.1 1763.11  4343.4 1749.30  4490.9 1744.38  4674.0 1740.16  4854.4 1738.18
  4934.5 1738.48  5029.2 1734.61  5029.7 1734.11  5040.2 1734.61  5040.5 1735.78
  5045.6 1737.06  5074.8 1739.70  5255.2 1742.65  5505.7 1755.17  5525.8 1755.08
  5535.8 1756.30  5555.8 1755.74  5666.1 1759.60  5786.3 1764.05  5803.1 1765.74
  5866.5 1767.45  5886.5 1769.30  5959.7 1771.41  6087.0 1777.55  6123.8 1780.51
#Mann=3,-1,0
  3996.2    0.15       0  5029.2    0.05       0  5040.2    0.15       0
Bank Sta=5029.2,5040.2
Exp/Cntr=0.3,0.1

Type RM Length L Ch R = 1,11788,1784,1784,1784
BEGIN DESCRIPTION:
Mapping XS 12b0c904
END DESCRIPTION:
XS GIS Cut Line= 3
      1672122.48      6967025.64      1672306.51      6967952.72
      1672389.83      6969213.00
#Sta/Elev= 30
  4071.6 1781.81  4104.6 1779.74  4176.0 1772.04  4212.3 1766.61  4277.9 1759.95
  4461.4 1749.70  4481.8 1747.43  4492.0 1744.80  4502.2 1743.56  4512.4 1743.84
  4524.4 1745.71  4626.7 1743.21  4736.7 1739.04  4882.6 1737.62  4928.6 1734.78
  4961.0 1735.19  4971.2 1733.78  4996.3 1733.15  4996.8 1732.65  5007.3 1733.15
  5022.1 1734.96  5068.4 1737.16  5412.9 1739.44  5643.4 1744.00  5743.6 1747.30
  5833.8 1753.23  5904.0 1754.23  5914.0 1755.23  6174.6 1763.07  6279.8 1767.91
#Mann=3,-1,0
  4071.6    0.15       0  4996.3    0.05       0  5007.3    0.15       0
Bank Sta=4996.3,5007.3
Exp/Cntr=0.3,0.1

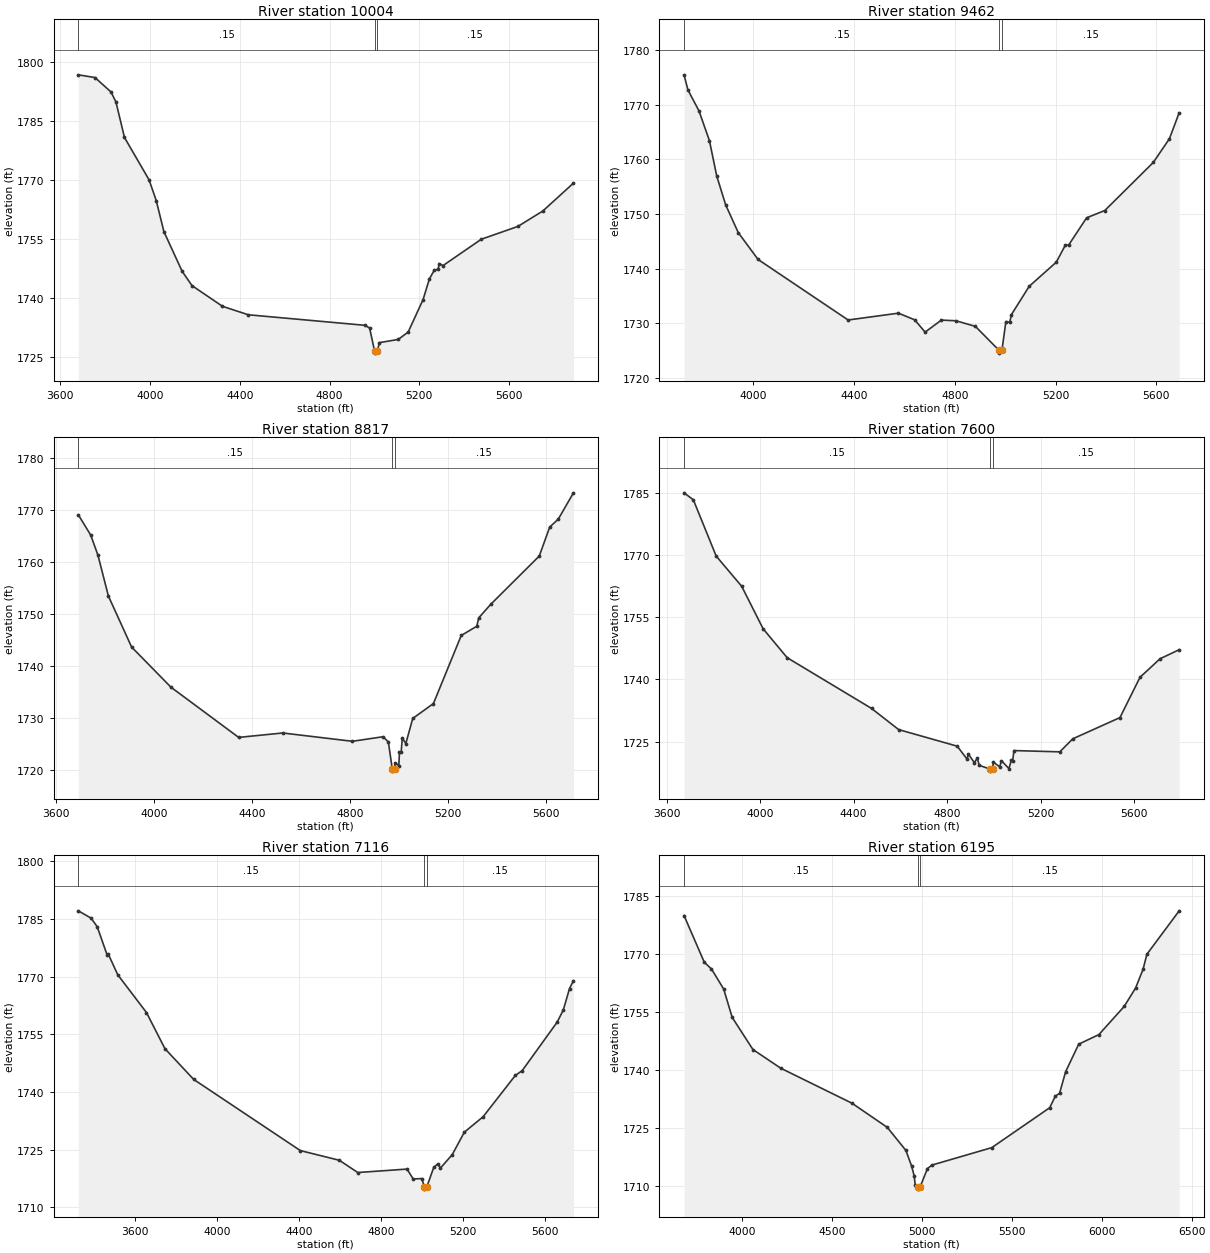
Type RM Length L Ch R = 1,10004,542,542,542
BEGIN DESCRIPTION:
Mapping XS cca2a93d
END DESCRIPTION:
XS GIS Cut Line= 3
      1671191.94      6967362.46      1671820.39      6968525.64
      1672222.97      6969313.44
#Sta/Elev= 30
  3680.3 1796.73  3754.7 1796.04  3826.1 1792.37  3848.0 1789.85  3886.1 1780.82
  3995.5 1770.08  4027.6 1764.81  4061.7 1756.93  4143.0 1746.84  4186.8 1743.21
  4322.9 1737.94  4438.0 1735.79  4956.7 1733.12  4978.6 1732.44  5000.9 1726.55
  5001.4 1726.05  5012.1 1726.55  5022.7 1728.72  5106.0 1729.52  5150.4 1731.39
  5217.0 1739.66  5244.9 1744.86  5267.1 1747.15  5283.7 1747.34  5289.3 1748.78
  5305.9 1748.29  5476.7 1754.98  5639.2 1758.22  5750.3 1762.13  5887.1 1769.22
#Mann=3,-1,0
  3680.3    0.15       0  5000.9    0.05       0  5012.1    0.15       0
Bank Sta=5000.9,5012.1
Exp/Cntr=0.3,0.1

Type RM Length L Ch R = 1,9462,645,645,645
BEGIN DESCRIPTION:
Mapping XS 94283c28
END DESCRIPTION:
XS GIS Cut Line= 3
      1670782.18      6967918.32      1671558.24      6968939.18
      1671980.08      6969478.19
#Sta/Elev= 30
  3724.4 1775.47  3740.1 1772.69  3783.7 1768.89  3825.4 1763.42  3854.4 1756.95
  3889.8 1751.69  3939.7 1746.62  4018.7 1741.69  4376.3 1730.62  4576.0 1731.87
  4640.4 1730.66  4682.1 1728.40  4746.5 1730.60  4804.3 1730.48  4881.7 1729.46
  4975.9 1725.06  4976.4 1724.56  4987.2 1725.06  5002.9 1730.34  5018.0 1730.19
  5025.1 1731.62  5095.6 1736.79  5203.2 1741.20  5238.5 1744.26  5252.9 1744.38
  5323.5 1749.31  5395.8 1750.65  5588.4 1759.44  5652.6 1763.79  5691.2 1768.53
#Mann=3,-1,0
  3724.4    0.15       0  4975.9    0.05       0  4987.2    0.15       0
Bank Sta=4975.9,4987.2
Exp/Cntr=0.3,0.1

Type RM Length L Ch R = 1,8817,1217,1217,1217
BEGIN DESCRIPTION:
Mapping XS 234521f3
END DESCRIPTION:
XS GIS Cut Line= 3
      1670487.95      6968204.83      1671172.83      6969327.20
      1671704.07      6969795.94
#Sta/Elev= 30
  3689.7 1769.14  3740.3 1765.25  3770.0 1761.37  3812.6 1753.52  3907.5 1743.70
  4068.3 1735.97  4345.0 1726.31  4525.2 1727.16  4809.6 1725.56  4935.2 1726.44
  4956.7 1725.43  4972.4 1720.32  4972.9 1719.82  4983.7 1720.32  4983.9 1721.40
  4999.4 1720.90  5002.1 1723.42  5008.9 1723.42  5013.7 1726.23  5027.9 1725.11
  5056.4 1729.96  5140.8 1732.82  5254.6 1745.93  5318.2 1747.70  5325.8 1749.30
  5375.1 1751.92  5573.4 1761.21  5616.0 1766.78  5651.2 1768.32  5713.0 1773.37
#Mann=3,-1,0
  3689.7    0.15       0  4972.4    0.05       0  4983.7    0.15       0
Bank Sta=4972.4,4983.7
Exp/Cntr=0.3,0.1

Type RM Length L Ch R = 1,7600,484,484,484
BEGIN DESCRIPTION:
Mapping XS 7ed38651
END DESCRIPTION:
XS GIS Cut Line= 3
      1669389.37      6969052.01      1670655.03      6969445.25
      1671397.21      6969721.29
#Sta/Elev= 30
  3674.8 1785.12  3714.6 1783.44  3812.3 1769.84  3921.5 1762.52  4012.9 1752.27
  4115.8 1745.27  4476.5 1733.01  4592.5 1727.89  4843.0 1723.88  4884.9 1720.77
  4890.8 1721.95  4916.3 1719.90  4928.6 1720.97  4937.3 1719.25  4982.7 1718.35
  4983.2 1717.85  4994.3 1718.35  4997.5 1720.02  5024.6 1718.89  5032.1 1720.36
  5064.1 1718.47  5074.6 1720.52  5079.9 1720.24  5085.5 1722.82  5281.7 1722.51
  5337.1 1725.66  5538.8 1730.79  5624.5 1740.53  5710.2 1745.01  5792.0 1747.20
#Mann=3,-1,0
  3674.8    0.15       0  4982.7    0.05       0  4994.3    0.15       0
Bank Sta=4982.7,4994.3
Exp/Cntr=0.3,0.1

Type RM Length L Ch R = 1,7116,921,921,921
BEGIN DESCRIPTION:
Mapping XS 752d7198
END DESCRIPTION:
XS GIS Cut Line= 3
      1669222.76      6969898.38      1670897.22      6969835.88
      1671634.17      6969895.77
#Sta/Elev= 30
  3324.0 1787.14  3386.3 1785.24  3416.3 1783.00  3464.7 1775.63  3469.7 1775.93
  3516.4 1770.50  3656.5 1760.67  3746.5 1751.27  3886.6 1743.27  4407.0 1724.74
  4597.1 1722.22  4687.2 1719.03  4927.4 1719.93  4957.4 1717.35  4999.6 1717.46
  5011.7 1715.21  5012.2 1714.71  5023.3 1715.21  5057.6 1720.36  5077.7 1721.29
  5090.1 1720.18  5147.9 1723.69  5207.0 1729.54  5298.4 1733.55  5455.9 1744.32
  5489.0 1745.55  5659.6 1758.17  5689.7 1761.35  5719.8 1766.91  5739.0 1768.95
#Mann=3,-1,0
  3324.0    0.15       0  5011.7    0.05       0  5023.3    0.15       0
Bank Sta=5011.7,5023.3
Exp/Cntr=0.3,0.1

Type RM Length L Ch R = 1,6195,951,951,951
BEGIN DESCRIPTION:
Mapping XS 25eaa5b1
END DESCRIPTION:
XS GIS Cut Line= 3
      1669221.64      6970832.19      1670502.90      6970491.04
      1671877.89      6970100.42
#Sta/Elev= 30
  3675.3 1780.07  3788.1 1767.97  3828.2 1766.23  3896.1 1761.03  3943.4 1753.69
  4058.7 1745.39  4214.0 1740.54  4610.1 1731.49  4806.7 1725.23  4910.2 1719.26
  4941.3 1715.28  4955.8 1712.77  4962.0 1710.34  4976.8 1709.76  4977.3 1709.26
  4988.6 1709.76  5030.0 1714.59  5055.4 1715.49  5388.0 1720.00  5710.3 1730.33
  5741.5 1733.33  5765.0 1734.05  5798.9 1739.66  5871.8 1746.78  5983.9 1749.25
  6124.7 1756.54  6188.5 1761.33  6230.1 1766.21  6250.9 1770.03  6430.6 1781.28
#Mann=3,-1,0
  3675.3    0.15       0  4976.8    0.05       0  4988.6    0.15       0
Bank Sta=4976.8,4988.6
Exp/Cntr=0.3,0.1