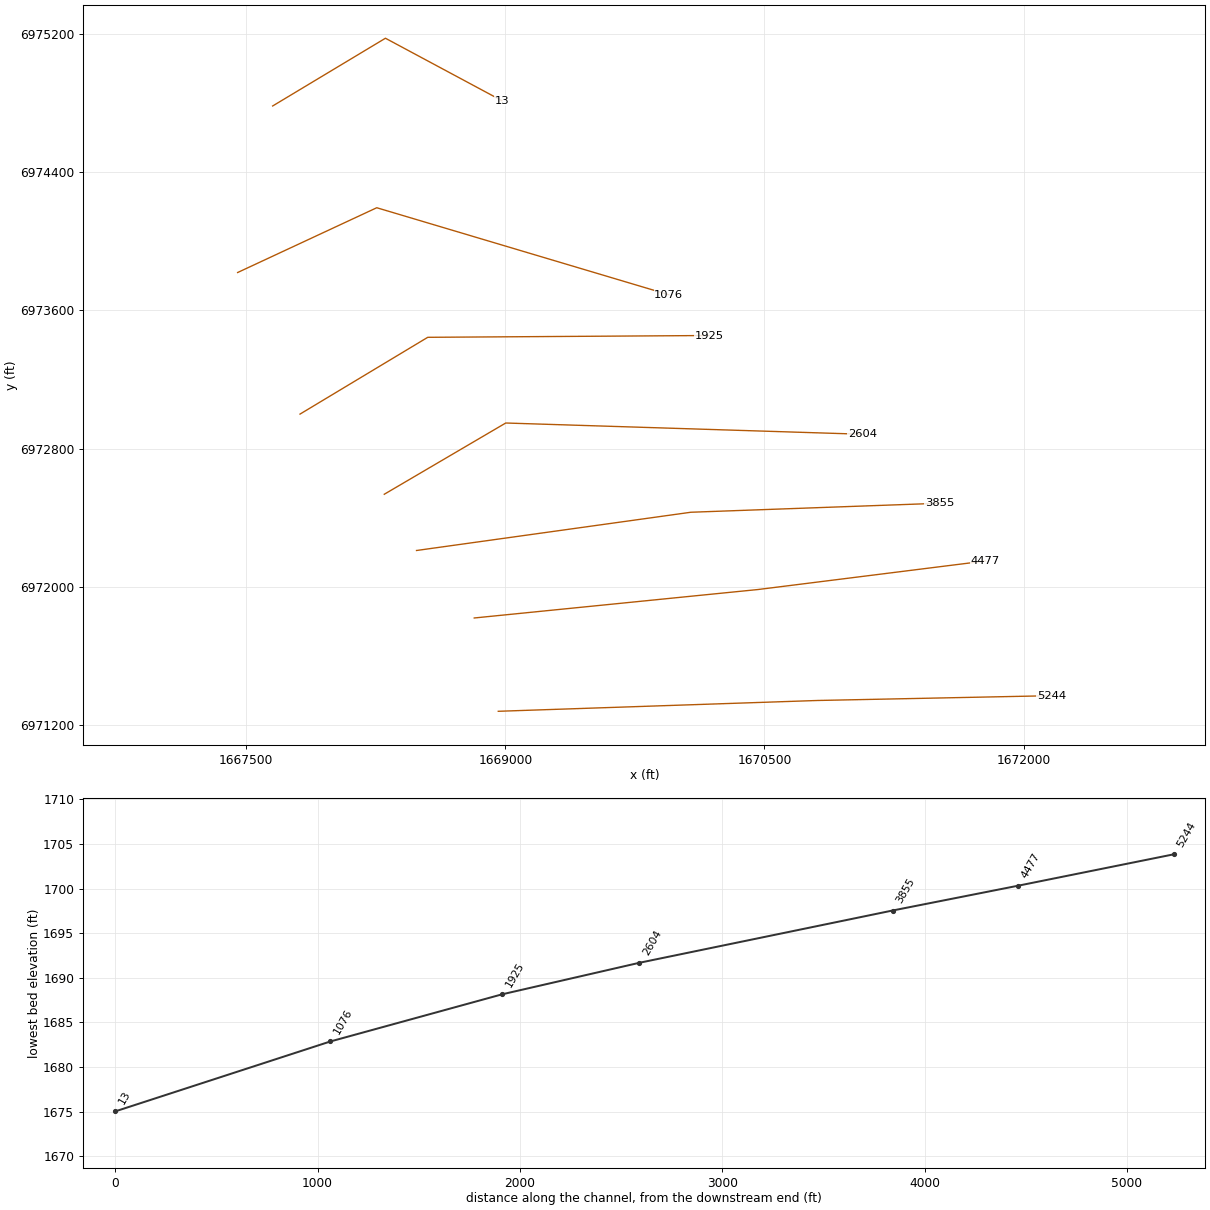
HEC-RAS study Chimney Creek 1156.prj: Chimney Creek 1156 Base Level Engineering

--- Chimney Creek 1156.g01 (geometry) --- (continued)

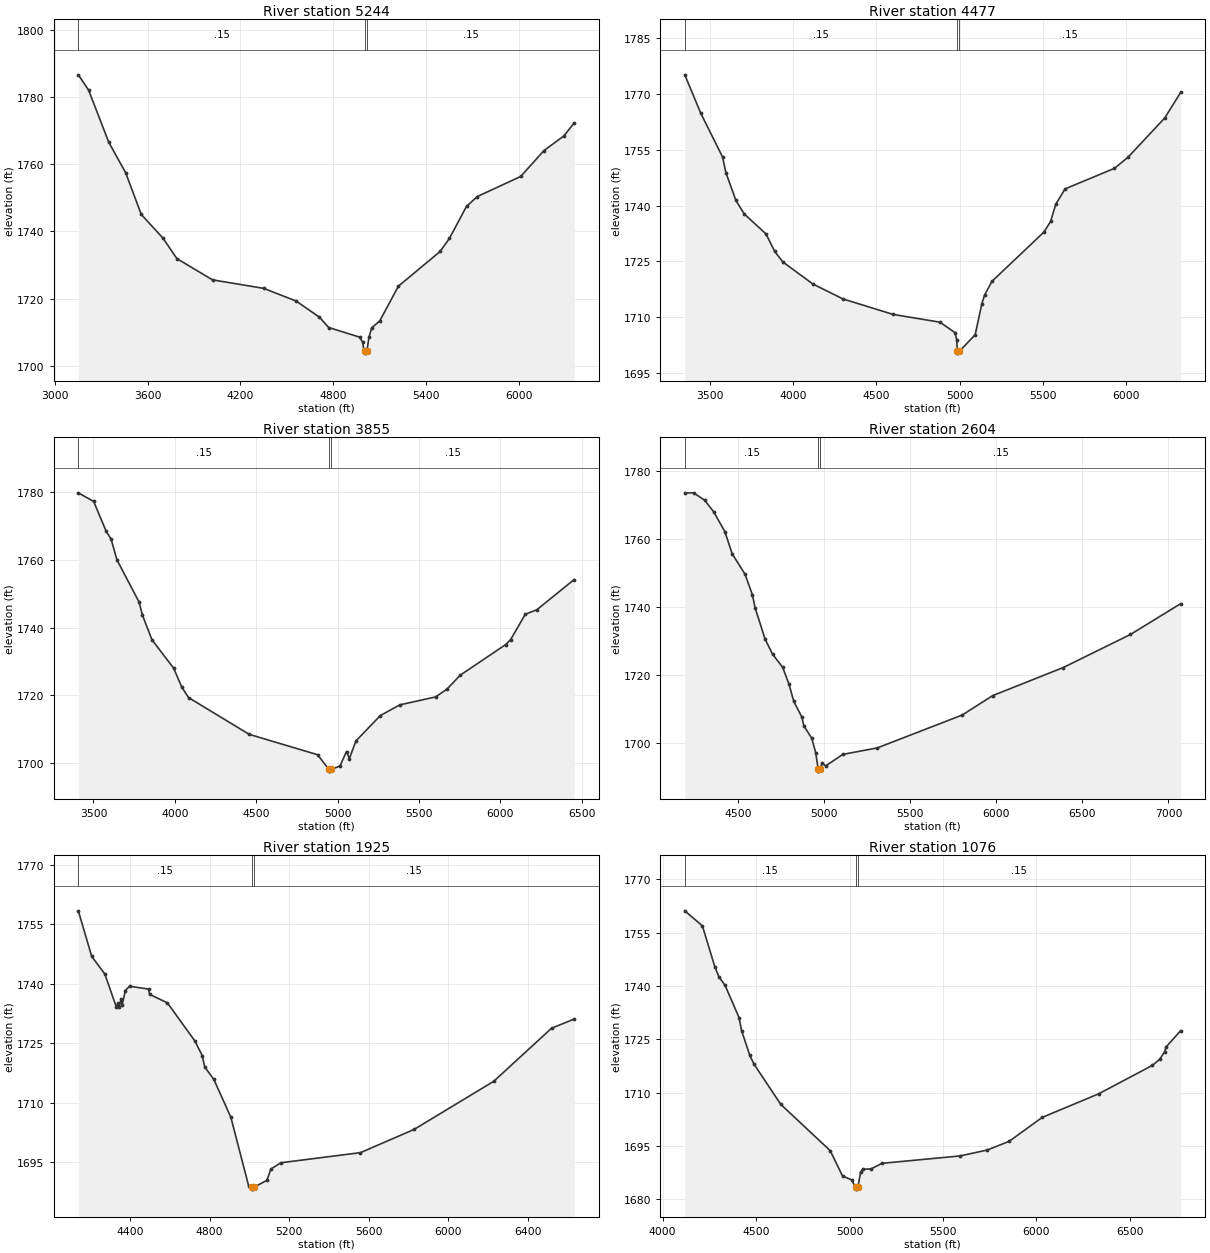
Type RM Length L Ch R = 1,5244,767,767,767
BEGIN DESCRIPTION:
Mapping XS 48963b7c
END DESCRIPTION:
XS GIS Cut Line= 3
      1668958.78      6971279.50      1670806.03      6971342.00
      1672160.14      6971369.77
#Sta/Elev= 30
  3152.7 1786.55  3219.0 1782.01  3349.0 1766.54  3459.1 1757.39  3559.1 1745.07
  3699.2 1738.04  3789.3 1731.94  4019.4 1725.62  4349.6 1723.10  4559.7 1719.33
  4709.8 1714.54  4769.8 1711.46  4970.0 1708.60  4990.0 1707.03  4998.0 1704.45
  5003.9 1704.35  5004.4 1703.85  5016.0 1704.35  5030.0 1708.56  5047.4 1711.35
  5100.0 1713.44  5220.0 1723.74  5490.1 1734.08  5550.1 1737.98  5660.1 1747.46
  5730.1 1750.39  6010.2 1756.35  6160.2 1764.04  6290.2 1768.43  6355.4 1772.28
#Mann=3,-1,0
  3152.7    0.15       0  5003.9    0.05       0  5016.0    0.15       0
Bank Sta=5003.9,5016
Exp/Cntr=0.3,0.1

Type RM Length L Ch R = 1,4477,622,622,622
BEGIN DESCRIPTION:
Mapping XS 6607e6fa
END DESCRIPTION:
XS GIS Cut Line= 3
      1668819.53      6971819.54      1670464.54      6971984.47
      1671779.68      6972149.41
#Sta/Elev= 30
  3349.2 1775.12  3445.2 1764.79  3575.8 1753.07  3595.9 1748.86  3656.2 1741.38
  3706.5 1737.73  3837.1 1732.37  3888.7 1727.73  3937.6 1724.86  4118.5 1718.92
  4299.4 1714.90  4600.9 1710.74  4882.3 1708.65  4972.8 1705.84  4982.7 1703.98
  4986.8 1700.84  4987.3 1700.34  4999.0 1700.84  5093.6 1705.28  5133.9 1713.63
  5150.2 1715.94  5194.4 1719.63  5506.8 1732.87  5547.2 1735.74  5577.4 1740.30
  5633.2 1744.46  5930.1 1749.99  6010.8 1752.92  6232.5 1763.53  6327.9 1770.39
#Mann=3,-1,0
  3349.2    0.15       0  4986.8    0.05       0  4999.0    0.15       0
Bank Sta=4986.8,4999
Exp/Cntr=0.3,0.1

Type RM Length L Ch R = 1,3855,1251,1251,1251
BEGIN DESCRIPTION:
Mapping XS cfc37ed3
END DESCRIPTION:
XS GIS Cut Line= 3
      1668485.34      6972210.16      1670073.91      6972431.52
      1671514.85      6972483.61
#Sta/Elev= 30
  3406.9 1779.84  3501.2 1777.28  3578.2 1768.44  3608.5 1766.13  3644.3 1760.00
  3780.1 1747.54  3800.3 1743.73  3859.0 1736.40  3992.2 1728.00  4042.6 1722.38
  4083.8 1719.30  4456.6 1708.42  4876.1 1702.41  4946.6 1698.05  4947.1 1697.55
  4958.9 1698.05  5013.9 1699.06  5054.3 1703.35  5072.0 1701.26  5112.0 1706.47
  5262.1 1713.99  5382.2 1717.15  5601.3 1719.49  5672.3 1721.83  5752.4 1725.91
  6032.6 1734.99  6062.6 1736.46  6152.7 1743.95  6222.7 1745.24  6452.7 1754.20
#Mann=3,-1,0
  3406.9    0.15       0  4946.6    0.05       0  4958.9    0.15       0
Bank Sta=4946.6,4958.9
Exp/Cntr=0.3,0.1

Type RM Length L Ch R = 1,2604,679,679,679
BEGIN DESCRIPTION:
Mapping XS 1eb39c04
END DESCRIPTION:
XS GIS Cut Line= 3
      1668298.75      6972535.70      1669001.86      6972948.02
      1671066.45      6972882.96
#Sta/Elev= 30
  4190.1 1773.49  4241.0 1773.53  4305.4 1771.36  4358.3 1767.94  4422.7 1762.13
  4465.6 1755.58  4540.0 1749.60  4582.9 1743.54  4598.6 1739.69  4657.2 1730.44
  4700.2 1726.06  4758.8 1722.22  4796.0 1717.18  4823.3 1712.18  4869.7 1707.65
  4881.9 1705.01  4927.7 1701.37  4950.4 1697.15  4965.6 1692.19  4966.1 1691.69
  4978.1 1692.19  4985.6 1693.99  5009.3 1693.25  5108.4 1696.62  5308.5 1698.52
  5801.6 1708.18  5978.8 1713.89  6389.0 1722.16  6779.2 1731.87  7070.8 1740.93
#Mann=3,-1,0
  4190.1    0.15       0  4965.6    0.05       0  4978.1    0.15       0
Bank Sta=4965.6,4978.1
Exp/Cntr=0.3,0.1

Type RM Length L Ch R = 1,1925,849,849,849
BEGIN DESCRIPTION:
Mapping XS cc6647fe
END DESCRIPTION:
XS GIS Cut Line= 3
      1667810.74      6972999.59      1668550.30      6973444.02
      1670178.74      6973454.44
#Sta/Elev= 30
  4140.4 1758.35  4207.4 1746.88  4273.7 1742.39  4332.0 1734.00  4339.5 1735.17
  4345.3 1733.98  4355.1 1736.12  4360.9 1734.60  4376.4 1738.25  4397.8 1739.34
  4493.0 1738.61  4498.8 1737.28  4588.2 1735.12  4726.2 1725.51  4763.1 1721.82
  4775.4 1718.96  4821.4 1715.82  4906.9 1706.26  4996.2 1688.96  5011.6 1688.65
  5012.1 1688.15  5024.2 1688.65  5087.9 1690.38  5107.9 1693.21  5157.9 1694.80
  5557.9 1697.35  5827.9 1703.22  6227.9 1715.36  6518.0 1728.73  6631.7 1731.05
#Mann=3,-1,0
  4140.4    0.15       0  5011.6    0.05       0  5024.2    0.15       0
Bank Sta=5011.6,5024.2
Exp/Cntr=0.3,0.1

Type RM Length L Ch R = 1,1076,1063,1063,1063
BEGIN DESCRIPTION:
Mapping XS b3995b31
END DESCRIPTION:
XS GIS Cut Line= 3
      1667449.58      6973819.01      1668255.16      6974194.02
      1669946.11      6973690.56
#Sta/Elev= 30
  4118.5 1761.16  4212.7 1756.93  4278.9 1745.47  4301.0 1742.60  4334.1 1740.18
  4409.0 1731.10  4422.3 1727.44  4466.4 1720.50  4488.7 1718.03  4631.9 1706.71
  4896.6 1693.68  4962.8 1686.53  5011.4 1685.47  5031.9 1683.36  5032.4 1682.86
  5044.6 1683.36  5059.1 1687.64  5069.5 1688.43  5116.1 1688.57  5173.9 1690.12
  5591.2 1692.20  5737.3 1693.87  5854.5 1696.33  6030.8 1703.04  6332.0 1709.65
  6620.8 1717.69  6659.2 1719.38  6686.8 1721.58  6692.4 1722.78  6771.4 1727.45
#Mann=3,-1,0
  4118.5    0.15       0  5031.9    0.05       0  5044.6    0.15       0
Bank Sta=5031.9,5044.6
Exp/Cntr=0.3,0.1

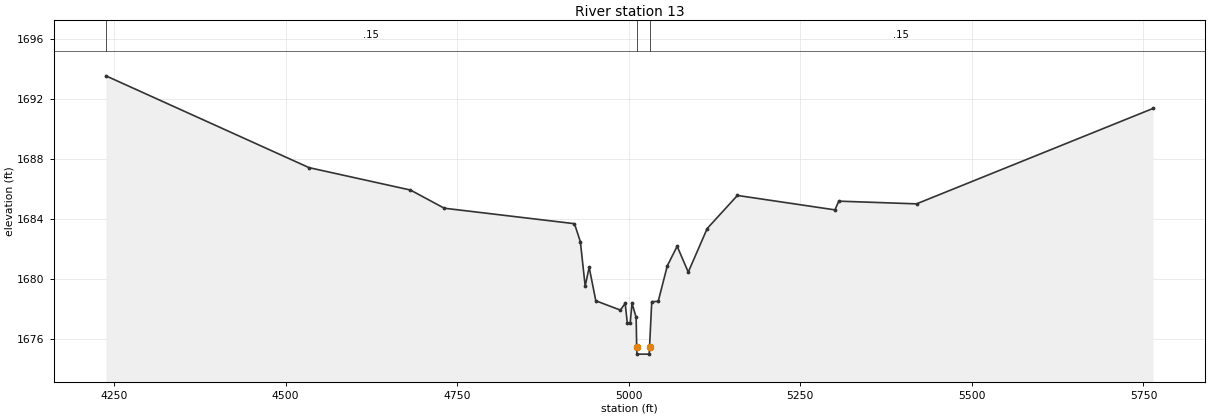
Type RM Length L Ch R = 1,13,0,0,0
BEGIN DESCRIPTION:
Chimney Creek 1156 1.0
END DESCRIPTION:
XS GIS Cut Line= 3
      1667652.37      6974782.92      1668305.38      6975175.04
      1668978.78      6974814.16
#Sta/Elev= 30
  4238.3 1693.54  4534.3 1687.43  4682.0 1685.94  4731.3 1684.73  4921.0 1683.70
  4929.6 1682.50  4936.6 1679.55  4942.4 1680.80  4952.1 1678.57  4987.9 1677.95
  4994.9 1678.40  4998.0 1677.08  5002.2 1677.08  5004.8 1678.40  5010.9 1677.46
  5011.6 1675.52  5012.1 1675.02  5029.9 1675.02  5030.4 1675.52  5033.6 1678.51
  5043.0 1678.53  5056.3 1680.90  5070.6 1682.20  5086.8 1680.48  5114.4 1683.38
  5158.4 1685.58  5300.5 1684.62  5306.1 1685.20  5419.4 1685.02  5764.0 1691.37
#Mann=3,-1,0
  4238.3    0.15       0  5011.6    0.05       0  5030.4    0.15       0
Bank Sta=5011.6,5030.4
Exp/Cntr=0.3,0.1

Chan Stop Cuts=-1