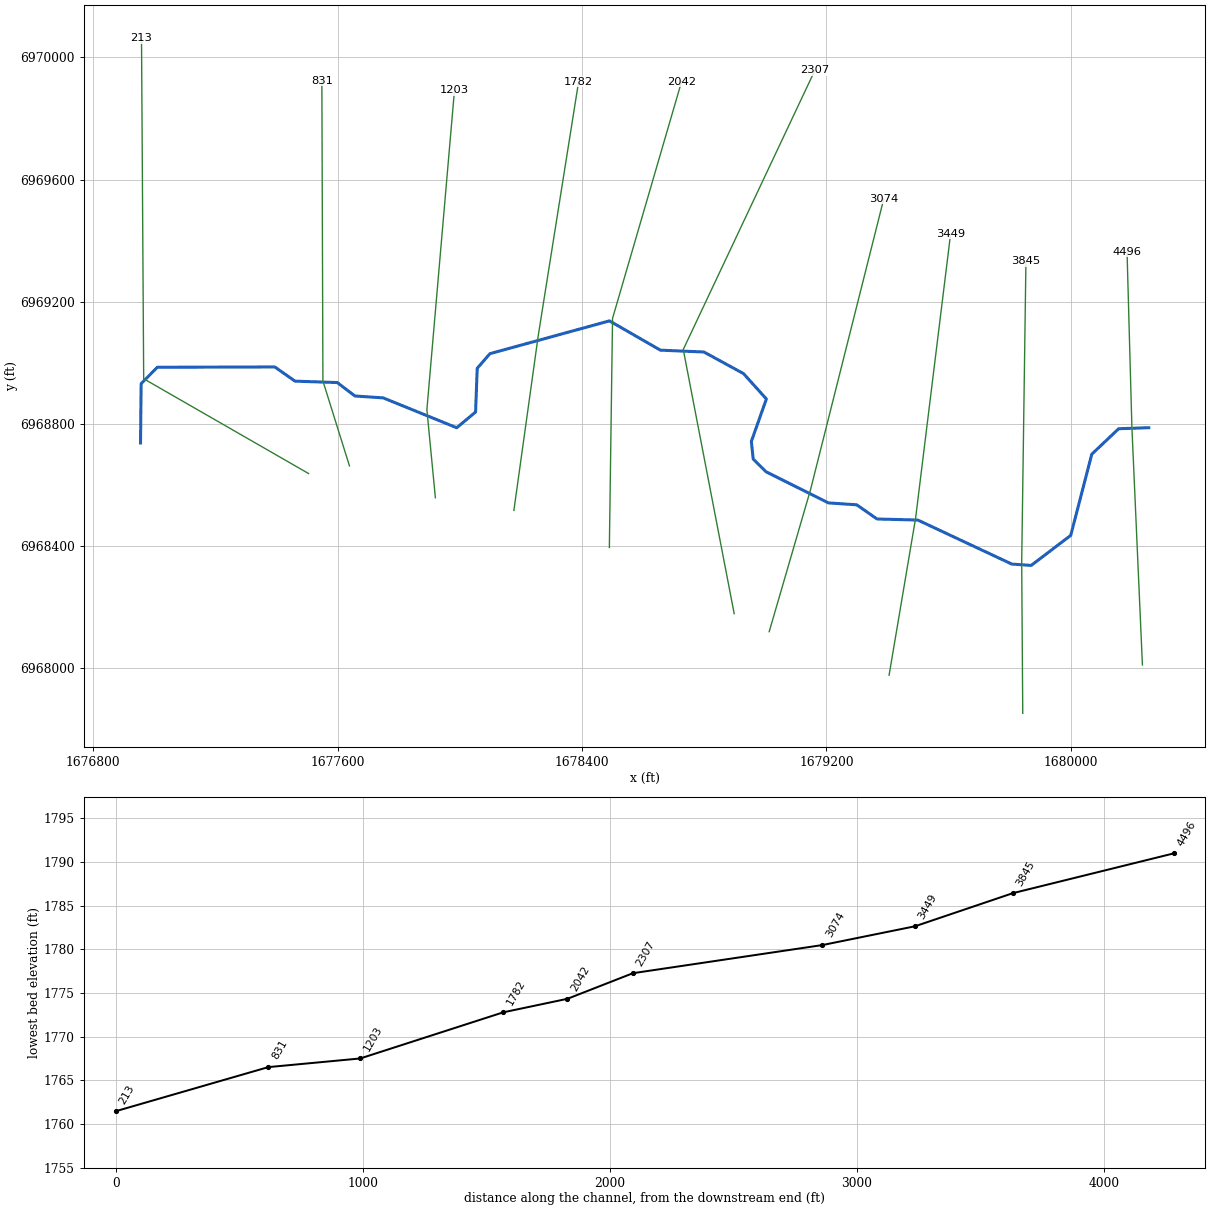
--- Chimney Creek 1157.prj (project) ---

Proj Title=Chimney Creek 1157 Base Level Engineering
Current Plan=p01
Default Exp/Contr=0.3,0.1
English Units
Geom File=g01
Flow File=f01
Plan File=p01
BEGIN DESCRIPTION:
Chimney Creek 1157
END DESCRIPTION:

--- Chimney Creek 1157.p01 (plan) ---

Plan Title=Multiple Run
Short Identifier=Multiple
Geom File=g01
Flow File=f01
Subcritical Flow
K Sum by GR= 0
Std Step Tol= 0.01
Critical Tol= 0.01
Num of Std Step Trials= 20
Max Error Tol= 0.3
Flow Tol Ratio= 0.001
Split Flow NTrial= 30
Split Flow Tol= 0.02
Split Flow Ratio= 0.02
Log Output Level= 0
Friction Slope Method= 1
Unsteady Friction Slope Method= 2
Unsteady Bridges Friction Slope Method= 1
Parabolic Critical Depth
Global Vel Dist=  1 , 1 , 1
Global Log Level= 0
CheckData=True
Encroach Param= -1, 0, 0, 0
BEGIN DESCRIPTION:
Multiple Run
END DESCRIPTION:

--- Chimney Creek 1157.f01 (steady flow) ---

Flow Title=Multiple
Number of Profiles=7
Profile Names=10-year,25-year,50-year,1pct_min,100-year,1pct_plu,500-year
River Rch & RM= Chimney Creek 11,Reach-1,4496
     225     307     373     226     450     899     666
River Rch & RM= Chimney Creek 11,Reach-1,3074
     261     358     438     267     532    1062     796
Boundary for River Rch & Prof#=Chimney Creek 11,Reach-1,1
Up Type=0
Dn Type=3
Dn Slope=0.005
Boundary for River Rch & Prof#=Chimney Creek 11,Reach-1,2
Up Type=0
Dn Type=3
Dn Slope=0.005
Boundary for River Rch & Prof#=Chimney Creek 11,Reach-1,3
Up Type=0
Dn Type=3
Dn Slope=0.005
Boundary for River Rch & Prof#=Chimney Creek 11,Reach-1,4
Up Type=0
Dn Type=3
Dn Slope=0.005
Boundary for River Rch & Prof#=Chimney Creek 11,Reach-1,5
Up Type=0
Dn Type=3
Dn Slope=0.005
Boundary for River Rch & Prof#=Chimney Creek 11,Reach-1,6
Up Type=0
Dn Type=3
Dn Slope=0.005
Boundary for River Rch & Prof#=Chimney Creek 11,Reach-1,7
Up Type=0
Dn Type=3
Dn Slope=0.005

--- Chimney Creek 1157.g01 (geometry) ---

Geom Title=Existing Conditions

River Reach=Chimney Creek 11,Reach-1
Reach XY= 30
      1680255.00      6968788.00      1680156.39      6968784.63
      1680068.39      6968701.33      1679999.48      6968435.56
      1679870.09      6968337.23      1679806.59      6968341.67
      1679499.06      6968485.73      1679365.51      6968489.23
      1679299.02      6968535.64      1679206.58      6968541.83
      1679002.41      6968643.72      1678960.29      6968685.32
      1678954.16      6968743.00      1679003.39      6968881.98
      1678928.53      6968965.01      1678799.07      6969035.75
      1678656.56      6969041.76      1678489.73      6969137.63
      1678098.50      6969030.28      1678056.98      6968982.35
      1678051.55      6968839.19      1677989.81      6968787.89
      1677749.43      6968885.53      1677656.60      6968891.86
      1677599.06      6968935.73      1677460.53      6968940.39
      1677394.50      6968986.78      1677010.23      6968985.92
      1676956.96      6968932.36      1676955.00      6968738.00

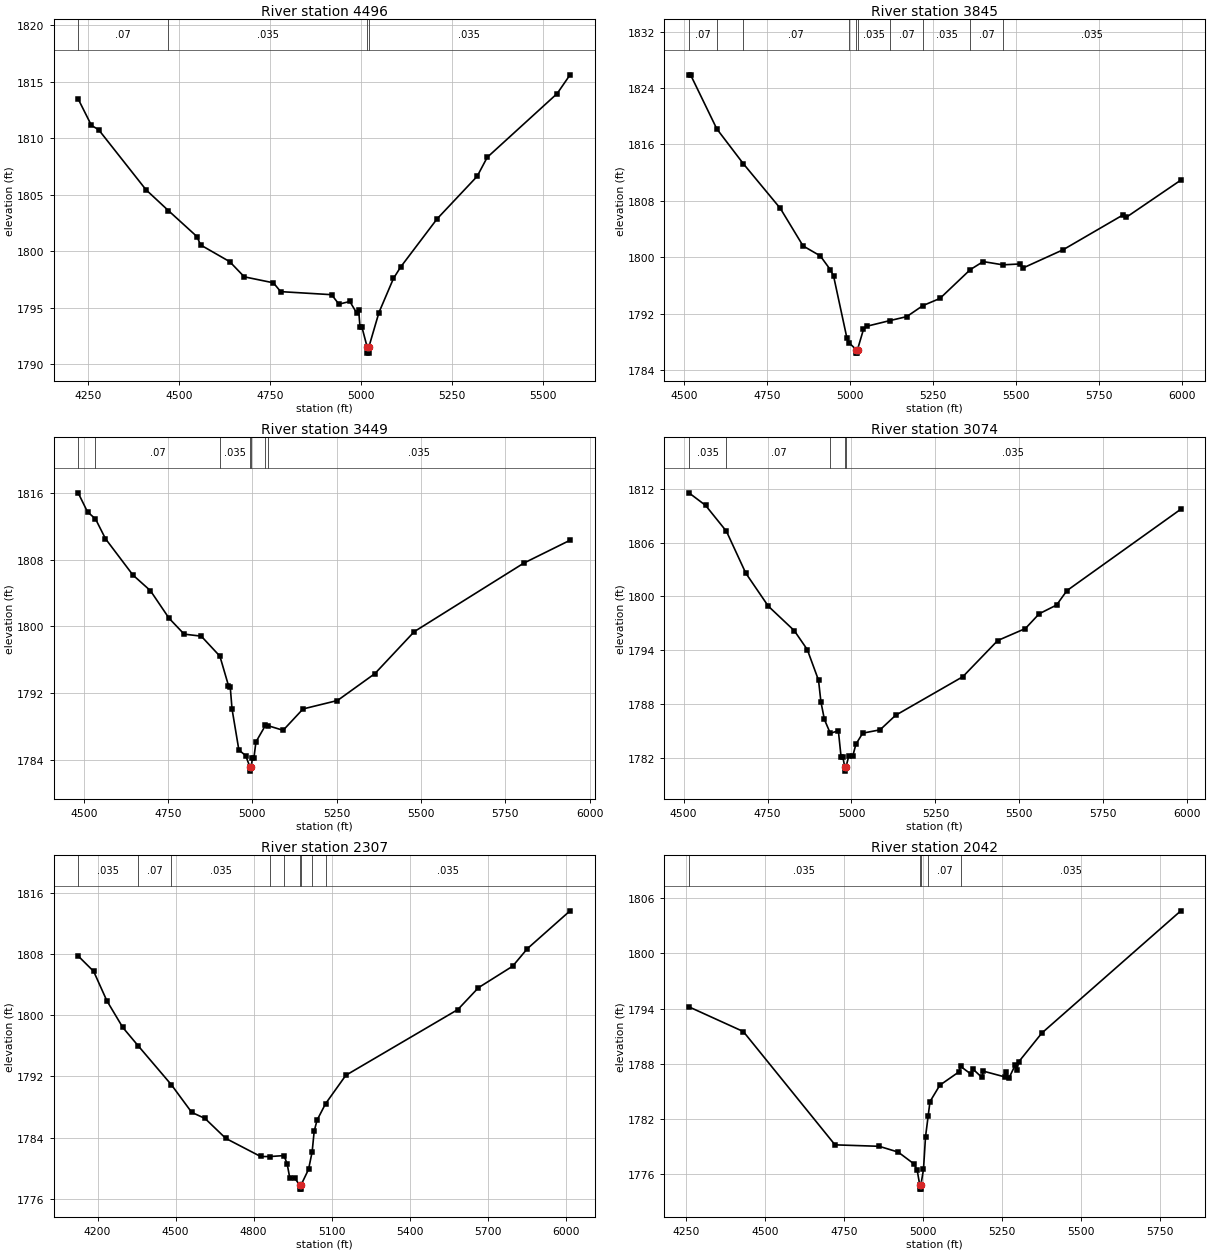
Type RM Length L Ch R = 1,4496,651,651,651
BEGIN DESCRIPTION:
Chimney Creek 1157 9.0
END DESCRIPTION:
XS GIS Cut Line= 3
      1680234.10      6968011.52      1680199.68      6968788.76
      1680183.77      6969363.44
#Sta/Elev= 30
  4222.0 1813.48  4258.5 1811.14  4278.5 1810.75  4408.7 1805.44  4470.2 1803.60
  4548.8 1801.30  4558.8 1800.56  4638.9 1799.08  4678.9 1797.74  4759.0 1797.21
  4779.0 1796.43  4919.2 1796.16  4939.2 1795.32  4969.2 1795.56  4988.5 1794.52
  4993.5 1794.80  4997.1 1793.34  5002.1 1793.34  5017.2 1791.49  5017.5 1790.99
  5021.0 1790.99  5021.2 1791.49  5049.3 1794.58  5089.3 1797.60  5109.3 1798.62
  5209.3 1802.87  5319.4 1806.63  5347.1 1808.31  5539.4 1813.95  5574.9 1815.61
#Mann=4,-1,0
  4222.0    0.07       0  4470.2   0.035       0  5017.2   0.035       0
  5021.2   0.035       0
Bank Sta=5017.2,5021.2
Exp/Cntr=0.3,0.1

Type RM Length L Ch R = 1,3845,396,396,396
BEGIN DESCRIPTION:
Mapping XS 0c64db63
END DESCRIPTION:
XS GIS Cut Line= 3
      1679842.44      6967853.01      1679838.97      6968346.08
      1679852.86      6969332.20
#Sta/Elev= 30
  4515.7 1825.87  4520.7 1825.87  4599.6 1818.21  4679.1 1813.29  4790.7 1806.94
  4859.0 1801.63  4910.7 1800.22  4940.7 1798.28  4950.7 1797.37  4990.7 1788.61
  4996.5 1787.94  5018.7 1786.94  5019.0 1786.44  5022.5 1786.44  5022.7 1786.94
  5040.7 1789.81  5050.7 1790.25  5121.0 1791.06  5170.7 1791.61  5219.2 1793.17
  5270.7 1794.19  5361.8 1798.27  5400.7 1799.41  5459.8 1798.95  5510.8 1799.07
  5520.8 1798.51  5640.8 1801.08  5820.8 1806.01  5830.8 1805.68  5995.0 1810.95
#Mann=10,-1,0
  4515.7    0.07       0  4599.6   0.035       0  4679.1    0.07       0
  4996.5   0.035       0  5018.7   0.035       0  5022.7   0.035       0
  5121.0    0.07       0  5219.2   0.035       0  5361.8    0.07       0
  5459.8   0.035       0
Bank Sta=5018.7,5022.7
Exp/Cntr=0.3,0.1

Type RM Length L Ch R = 1,3449,375,375,375
BEGIN DESCRIPTION:
Mapping XS 4fc133b8
END DESCRIPTION:
XS GIS Cut Line= 3
      1679404.94      6967978.00      1679491.75      6968491.91
      1679606.33      6969422.49
#Sta/Elev= 30
  4483.5 1815.99  4511.4 1813.70  4534.9 1812.87  4564.6 1810.49  4645.8 1806.15
  4697.8 1804.27  4753.2 1800.96  4797.9 1799.06  4848.6 1798.82  4903.9 1796.42
  4929.4 1792.89  4934.5 1792.77  4939.9 1790.09  4960.2 1785.18  4980.4 1784.51
  4992.9 1783.15  4993.2 1782.65  4996.9 1783.15  5000.2 1784.20  5004.7 1784.20
  5010.8 1786.15  5039.0 1788.13  5045.4 1788.11  5091.4 1787.54  5150.5 1790.10
  5252.6 1791.11  5363.5 1794.33  5480.3 1799.36  5805.2 1807.57  5942.3 1810.31
#Mann=7,-1,0
  4483.5   0.035       0  4534.9    0.07       0  4903.9   0.035       0
  4992.9   0.035       0  4996.9   0.035       0  5039.0    0.07       0
  5045.4   0.035       0
Bank Sta=4992.9,4996.9
Exp/Cntr=0.3,0.1

Type RM Length L Ch R = 1,3074,767,767,767
BEGIN DESCRIPTION:
Mapping XS ba093f6f
END DESCRIPTION:
XS GIS Cut Line= 3
      1679012.58      6968120.40      1679148.00      6968585.66
      1679387.59      6969537.09
#Sta/Elev= 30
  4515.6 1811.57  4565.2 1810.17  4627.5 1807.27  4685.1 1802.60  4752.1 1798.92
  4829.6 1796.18  4868.3 1794.07  4901.8 1790.65  4908.9 1788.24  4919.3 1786.27
  4936.9 1784.72  4960.9 1785.01  4968.9 1782.12  4974.1 1782.11  4979.8 1781.00
  4980.0 1780.50  4983.8 1781.00  4992.2 1782.22  5003.9 1782.19  5013.2 1783.51
  5033.5 1784.74  5085.1 1785.11  5131.4 1786.73  5331.7 1791.04  5435.7 1795.08
  5518.2 1796.42  5559.4 1798.07  5611.0 1799.04  5641.9 1800.65  5981.3 1809.74
#Mann=5,-1,0
  4515.6   0.035       0  4627.5    0.07       0  4936.9   0.035       0
  4979.8   0.035       0  4983.8   0.035       0
Bank Sta=4979.8,4983.8
Exp/Cntr=0.3,0.1

Type RM Length L Ch R = 1,2307,265,265,265
BEGIN DESCRIPTION:
Mapping XS 2f65a61f
END DESCRIPTION:
XS GIS Cut Line= 3
      1678897.99      6968179.45      1678731.33      6969043.99
      1679161.90      6969957.22
#Sta/Elev= 30
  4125.6 1807.72  4185.2 1805.71  4236.1 1801.86  4297.3 1798.38  4355.8 1796.01
  4484.2 1790.89  4562.0 1787.30  4613.0 1786.51  4692.7 1783.91  4826.8 1781.54
  4861.1 1781.53  4916.4 1781.66  4928.7 1780.59  4938.9 1778.72  4957.2 1778.74
  4977.5 1777.78  4977.8 1777.28  4981.4 1777.28  4981.6 1777.78  5011.0 1779.87
  5024.8 1782.16  5032.6 1784.85  5043.7 1786.29  5076.3 1788.43  5154.2 1792.14
  5584.5 1800.72  5663.9 1803.58  5795.1 1806.38  5851.7 1808.67  6015.7 1813.61
#Mann=9,-1,0
  4125.6   0.035       0  4355.8    0.07       0  4484.2   0.035       0
  4861.1    0.07       0  4916.4   0.035       0  4977.5   0.035       0
  4981.6   0.035       0  5024.8    0.07       0  5076.3   0.035       0
Bank Sta=4977.5,4981.6
Exp/Cntr=0.3,0.1

Type RM Length L Ch R = 1,2042,260,260,260
BEGIN DESCRIPTION:
Mapping XS 8b3b4e0d
END DESCRIPTION:
XS GIS Cut Line= 3
      1678489.45      6968395.79      1678499.87      6969145.74
      1678725.57      6969920.09
#Sta/Elev= 30
  4260.1 1794.19  4432.3 1791.50  4722.4 1779.17  4862.4 1779.01  4922.4 1778.38
  4972.4 1777.09  4982.4 1776.42  4990.3 1774.85  4990.6 1774.35  4994.2 1774.35
  4994.4 1774.85  5002.4 1776.50  5008.8 1780.04  5017.1 1782.28  5022.9 1783.87
  5054.1 1785.66  5114.6 1787.11  5119.8 1787.71  5153.3 1786.85  5158.5 1787.43
  5186.8 1786.52  5192.0 1787.19  5259.0 1786.57  5264.2 1787.12  5272.9 1786.44
  5292.5 1787.84  5297.7 1787.28  5304.1 1788.22  5377.0 1791.34  5816.7 1804.64
#Mann=5,-1,0
  4260.1   0.035       0  4990.3   0.035       0  4994.4   0.035       0
  5017.1    0.07       0  5119.8   0.035       0
Bank Sta=4990.3,4994.4
Exp/Cntr=0.3,0.1

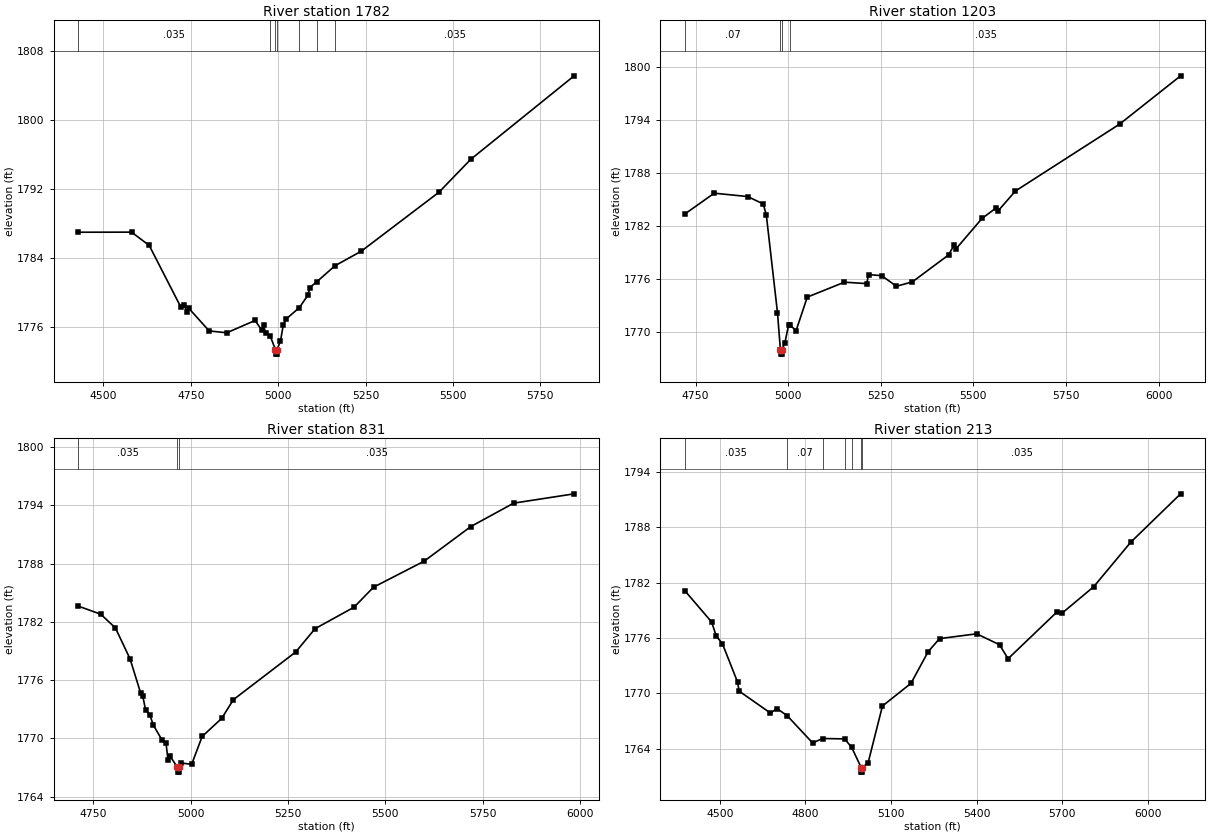
Type RM Length L Ch R = 1,1782,579,579,579
BEGIN DESCRIPTION:
Mapping XS b4f1f15b
END DESCRIPTION:
XS GIS Cut Line= 3
      1678176.95      6968517.29      1678256.81      6969090.18
      1678388.75      6969920.02
#Sta/Elev= 30
  4428.0 1786.97  4580.2 1786.98  4630.7 1785.44  4721.5 1778.25  4731.6 1778.46
  4738.2 1777.71  4743.3 1778.16  4802.3 1775.50  4852.8 1775.28  4933.6 1776.71
  4952.9 1775.59  4958.0 1776.14  4963.8 1775.29  4977.5 1774.87  4992.0 1773.30
  4992.3 1772.80  4996.0 1772.80  4996.2 1773.30  5006.4 1774.32  5014.4 1776.20
  5023.1 1776.90  5060.5 1778.21  5085.2 1779.67  5090.4 1780.54  5110.3 1781.21
  5162.6 1783.08  5237.1 1784.75  5459.9 1791.62  5551.0 1795.45  5846.7 1805.15
#Mann=7,-1,0
  4428.0   0.035       0  4977.5    0.07       0  4992.0    0.07       0
  4996.2    0.07       0  5060.5   0.035       0  5110.3    0.07       0
  5162.6   0.035       0
Bank Sta=4992,4996.2
Exp/Cntr=0.3,0.1

Type RM Length L Ch R = 1,1203,372,372,372
BEGIN DESCRIPTION:
Mapping XS a30e11ac
END DESCRIPTION:
XS GIS Cut Line= 3
      1677920.01      6968558.91      1677892.23      6968847.13
      1677982.51      6969892.28
#Sta/Elev= 30
  4720.8 1783.37  4800.3 1785.73  4890.7 1785.35  4932.6 1784.51  4940.9 1783.26
  4971.0 1772.22  4978.9 1768.02  4979.2 1767.52  4982.9 1767.52  4983.2 1768.02
  4991.1 1768.82  5001.2 1770.85  5005.7 1770.77  5021.3 1770.18  5051.4 1773.97
  5151.7 1775.66  5211.9 1775.50  5216.9 1776.52  5252.1 1776.40  5292.3 1775.20
  5335.3 1775.70  5432.8 1778.74  5448.6 1779.92  5453.6 1779.46  5523.1 1782.87
  5561.9 1784.08  5566.9 1783.74  5613.5 1785.98  5894.5 1793.54  6059.4 1799.01
#Mann=4,-1,0
  4720.8    0.07       0  4978.9    0.07       0  4983.2    0.07       0
  5005.7   0.035       0
Bank Sta=4978.9,4983.2
Exp/Cntr=0.3,0.1

Type RM Length L Ch R = 1,831,618,618,618
BEGIN DESCRIPTION:
Mapping XS 436786c7
END DESCRIPTION:
XS GIS Cut Line= 3
      1677638.75      6968663.13      1677551.95      6968940.88
      1677548.48      6969923.27
#Sta/Elev= 30
  4711.7 1783.63  4769.2 1782.80  4807.0 1781.38  4844.7 1778.18  4871.9 1774.65
  4877.2 1774.37  4884.4 1772.93  4894.9 1772.46  4904.4 1771.37  4926.3 1769.86
  4936.8 1769.57  4942.1 1767.73  4947.4 1768.17  4966.1 1767.03  4966.4 1766.53
  4970.2 1766.53  4970.4 1767.03  4974.6 1767.48  5002.7 1767.33  5029.8 1770.21
  5079.8 1772.06  5109.8 1773.99  5269.8 1778.90  5319.8 1781.31  5419.8 1783.52
  5469.8 1785.58  5599.8 1788.26  5719.8 1791.83  5829.8 1794.24  5985.1 1795.20
#Mann=3,-1,0
  4711.7   0.035       0  4966.1   0.035       0  4970.4   0.035       0
Bank Sta=4966.1,4970.4
Exp/Cntr=0.3,0.1

Type RM Length L Ch R = 1,213,0,0,0
BEGIN DESCRIPTION:
Chimney Creek 1157 1.0
END DESCRIPTION:
XS GIS Cut Line= 3
      1677505.02      6968637.99      1676965.32      6968948.18
      1676958.20      6970062.36
#Sta/Elev= 30
  4377.5 1781.13  4471.7 1777.73  4487.5 1776.22  4509.1 1775.40  4562.1 1771.25
  4568.0 1770.25  4677.4 1767.88  4700.5 1768.36  4736.1 1767.59  4825.3 1764.64
  4860.0 1765.12  4937.3 1765.08  4962.2 1764.15  4995.1 1761.98  4995.4 1761.48
  4999.2 1761.48  4999.5 1761.98  5019.8 1762.52  5069.8 1768.64  5169.8 1771.10
  5229.8 1774.52  5269.8 1775.94  5399.8 1776.46  5479.8 1775.28  5509.8 1773.76
  5679.8 1778.79  5699.8 1778.72  5809.8 1781.56  5939.8 1786.39  6114.2 1791.62
#Mann=7,-1,0
  4377.5   0.035       0  4736.1    0.07       0  4860.0   0.035       0
  4937.3    0.07       0  4962.2   0.035       0  4995.1   0.035       0
  4999.5   0.035       0
Bank Sta=4995.1,4999.5
Exp/Cntr=0.3,0.1

Chan Stop Cuts=-1