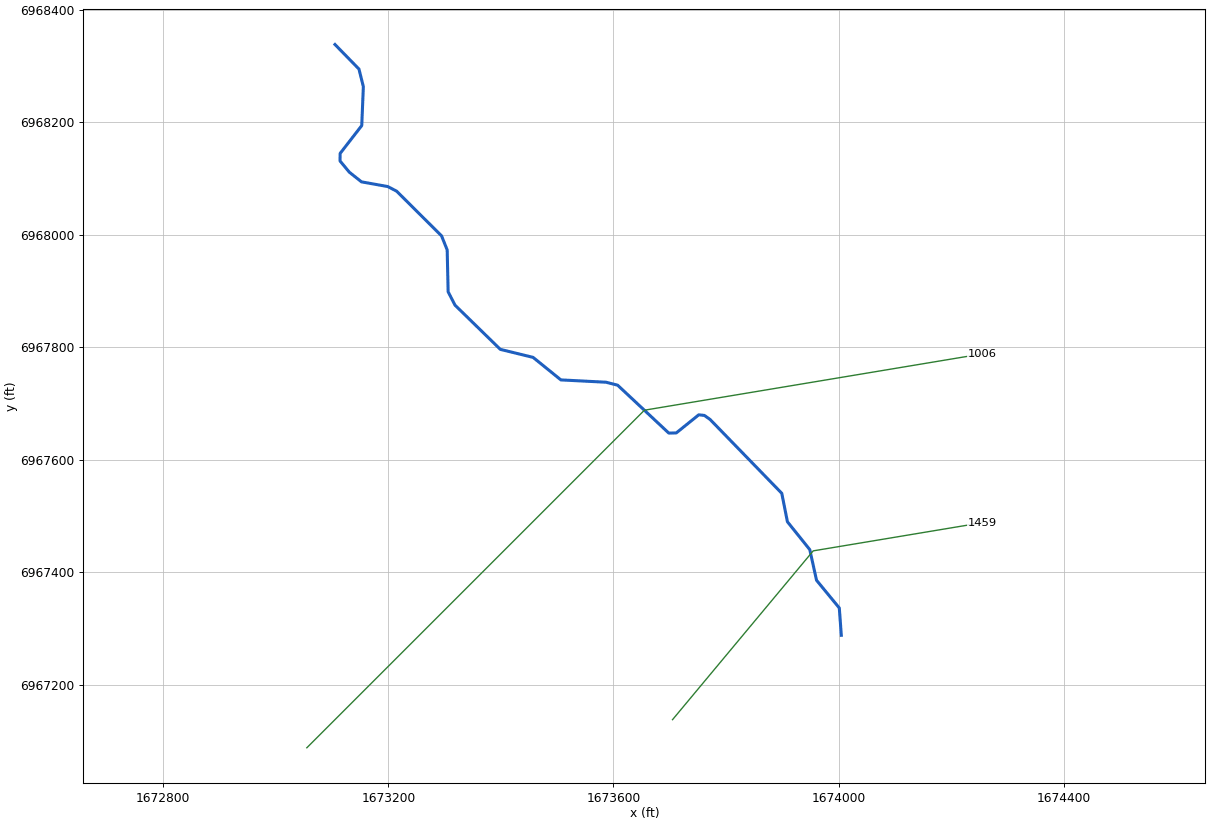
--- Chimney Creek 1158.prj (project) ---

Proj Title=Chimney Creek 1158 Base Level Engineering
Current Plan=p01
Default Exp/Contr=0.3,0.1
English Units
Geom File=g01
Flow File=f01
Plan File=p01
BEGIN DESCRIPTION:
Chimney Creek 1158
END DESCRIPTION:

--- Chimney Creek 1158.p01 (plan) ---

Plan Title=Multiple Run
Short Identifier=Multiple
Geom File=g01
Flow File=f01
Subcritical Flow
K Sum by GR= 0
Std Step Tol= 0.01
Critical Tol= 0.01
Num of Std Step Trials= 20
Max Error Tol= 0.3
Flow Tol Ratio= 0.001
Split Flow NTrial= 30
Split Flow Tol= 0.02
Split Flow Ratio= 0.02
Log Output Level= 0
Friction Slope Method= 1
Unsteady Friction Slope Method= 2
Unsteady Bridges Friction Slope Method= 1
Parabolic Critical Depth
Global Vel Dist=  1 , 1 , 1
Global Log Level= 0
CheckData=True
Encroach Param= -1, 0, 0, 0
BEGIN DESCRIPTION:
Multiple Run
END DESCRIPTION:

--- Chimney Creek 1158.f01 (steady flow) ---

Flow Title=Multiple
Number of Profiles=7
Profile Names=10-year,25-year,50-year,1pct_min,100-year,1pct_plu,500-year
River Rch & RM= Chimney Creek 11,Reach-1,1459
     279     388     479     295     589    1175     898
Boundary for River Rch & Prof#=Chimney Creek 11,Reach-1,1
Up Type=0
Dn Type=3
Dn Slope=0.005
Boundary for River Rch & Prof#=Chimney Creek 11,Reach-1,2
Up Type=0
Dn Type=3
Dn Slope=0.005
Boundary for River Rch & Prof#=Chimney Creek 11,Reach-1,3
Up Type=0
Dn Type=3
Dn Slope=0.005
Boundary for River Rch & Prof#=Chimney Creek 11,Reach-1,4
Up Type=0
Dn Type=3
Dn Slope=0.005
Boundary for River Rch & Prof#=Chimney Creek 11,Reach-1,5
Up Type=0
Dn Type=3
Dn Slope=0.005
Boundary for River Rch & Prof#=Chimney Creek 11,Reach-1,6
Up Type=0
Dn Type=3
Dn Slope=0.005
Boundary for River Rch & Prof#=Chimney Creek 11,Reach-1,7
Up Type=0
Dn Type=3
Dn Slope=0.005

--- Chimney Creek 1158.g01 (geometry) ---

Geom Title=Existing Conditions

River Reach=Chimney Creek 11,Reach-1
Reach XY= 30
      1674005.00      6967288.00      1674001.40      6967336.51
      1673960.95      6967385.75      1673948.93      6967440.20
      1673909.19      6967489.74      1673899.17      6967540.30
      1673771.67      6967671.61      1673761.67      6967678.70
      1673751.67      6967679.84      1673711.67      6967647.62
      1673698.34      6967647.32      1673607.43      6967732.45
      1673586.72      6967737.74      1673506.59      6967741.83
      1673457.17      6967781.86      1673398.92      6967796.13
      1673318.39      6967874.67      1673306.16      6967898.48
      1673304.48      6967972.79      1673294.49      6967997.81
      1673214.67      6968077.23      1673198.88      6968085.47
      1673152.15      6968093.85      1673130.59      6968110.99
      1673114.01      6968130.98      1673114.22      6968144.38
      1673152.63      6968193.87      1673155.47      6968263.00
      1673147.64      6968294.32      1673105.00      6968338.00

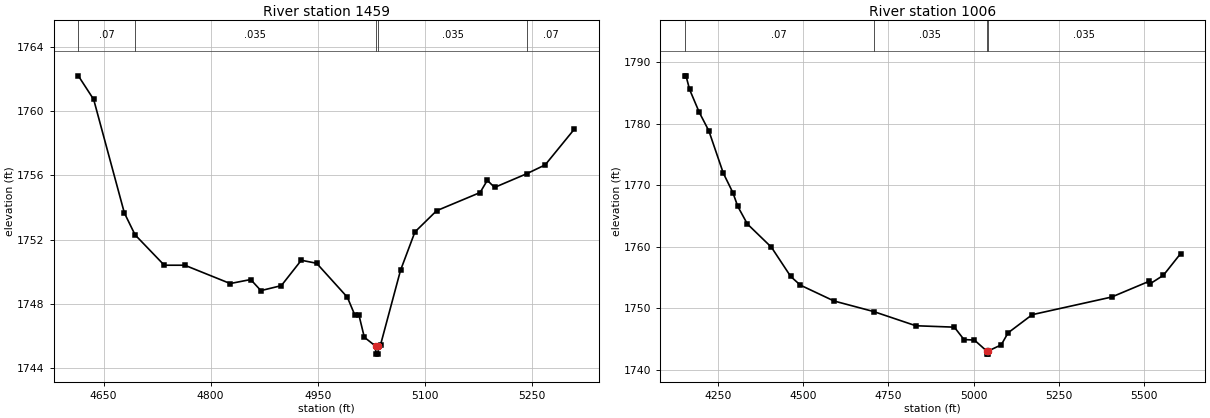
Type RM Length L Ch R = 1,1459,453,453,453
BEGIN DESCRIPTION:
Chimney Creek 1158 2.0
END DESCRIPTION:
XS GIS Cut Line= 3
      1673704.99      6967137.99      1673955.00      6967438.00
      1674255.03      6967488.01
#Sta/Elev= 30
  4614.7 1762.19  4636.2 1760.72  4679.2 1753.66  4694.2 1752.30  4735.1 1750.41
  4763.8 1750.41  4827.5 1749.27  4856.2 1749.52  4870.5 1748.83  4899.1 1749.14
  4927.1 1750.72  4948.6 1750.53  4991.6 1748.42  5002.0 1747.32  5007.8 1747.32
  5015.4 1745.93  5031.1 1745.38  5031.4 1744.88  5034.9 1744.88  5035.1 1745.38
  5038.2 1745.47  5066.1 1750.09  5086.3 1752.48  5116.7 1753.80  5177.6 1754.93
  5187.7 1755.69  5197.9 1755.25  5242.9 1756.10  5268.8 1756.65  5309.4 1758.86
#Mann=5,-1,0
  4614.7    0.07       0  4694.2   0.035       0  5031.1   0.035       0
  5035.1   0.035       0  5242.9    0.07       0
Bank Sta=5031.1,5035.1
Exp/Cntr=0.3,0.1

Type RM Length L Ch R = 1,1006,0,0,0
BEGIN DESCRIPTION:
Chimney Creek 1158 1.0
END DESCRIPTION:
XS GIS Cut Line= 3
      1673055.02      6967088.02      1673655.00      6967688.00
      1674255.02      6967788.00
#Sta/Elev= 30
  4151.6 1787.75  4155.1 1787.75  4165.7 1785.53  4194.0 1781.83  4222.3 1778.81
  4264.7 1771.95  4293.0 1768.76  4307.1 1766.56  4335.4 1763.69  4406.1 1759.91
  4462.7 1755.17  4491.0 1753.76  4590.0 1751.18  4706.2 1749.47  4830.4 1747.16
  4943.5 1746.93  4971.8 1744.92  5002.6 1744.83  5038.7 1743.05  5038.9 1742.55
  5042.4 1742.55  5042.7 1743.05  5081.2 1744.05  5101.5 1746.01  5172.4 1748.96
  5405.6 1751.82  5514.6 1754.35  5519.7 1754.01  5557.7 1755.35  5608.4 1758.88
#Mann=4,-1,0
  4151.6    0.07       0  4706.2   0.035       0  5038.7   0.035       0
  5042.7   0.035       0
Bank Sta=5038.7,5042.7
Exp/Cntr=0.3,0.1

Chan Stop Cuts=-1