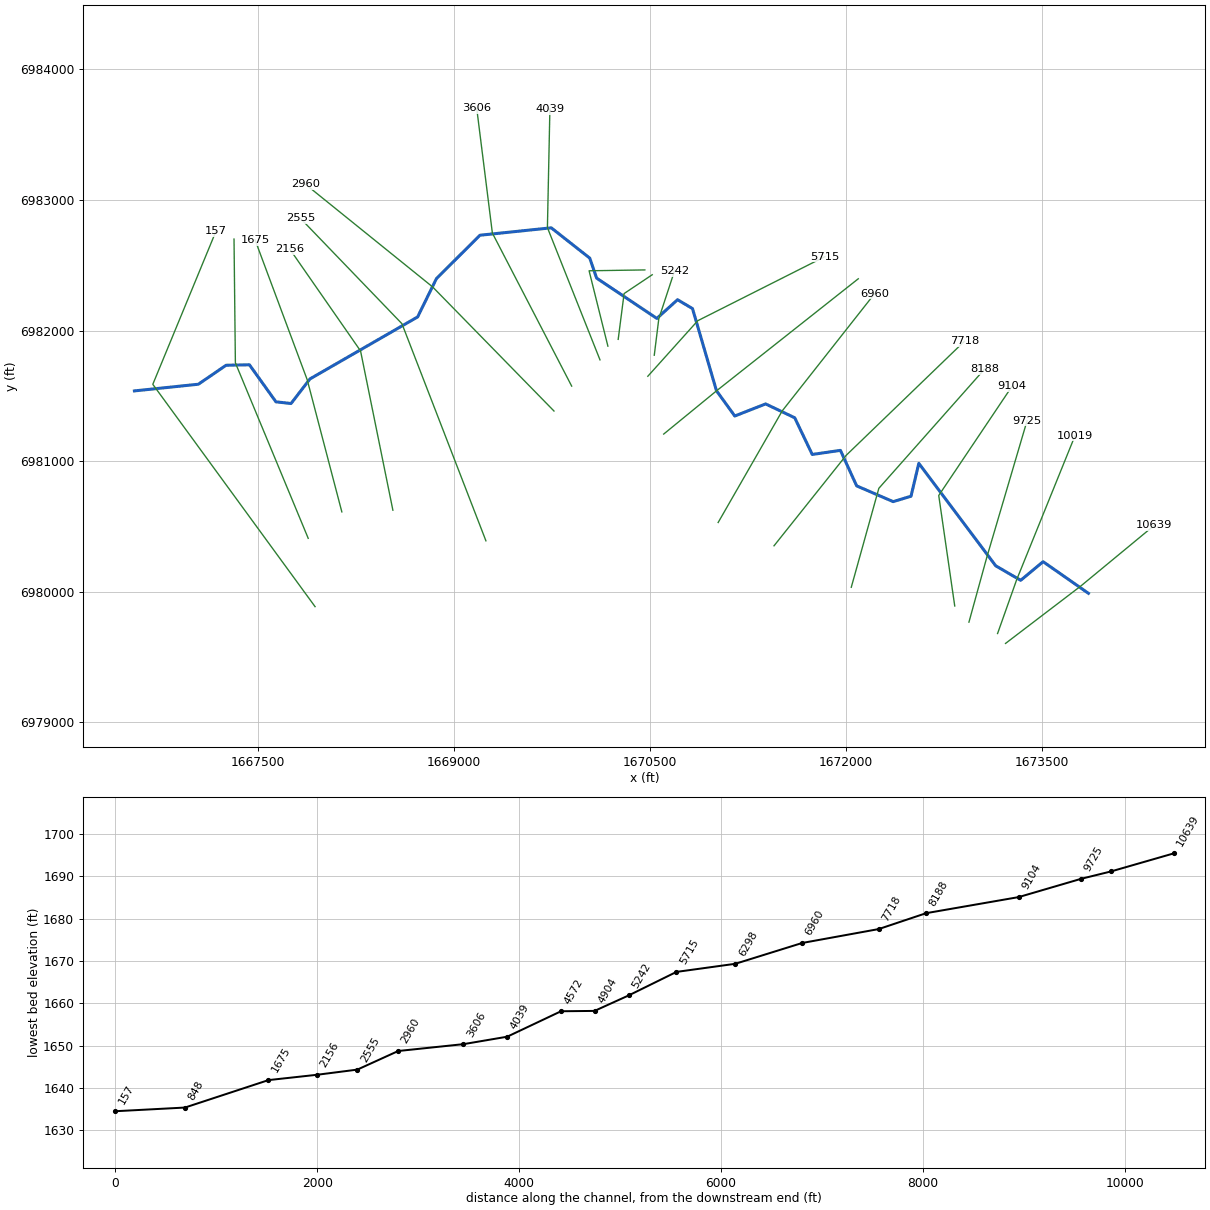
--- Chimney Creek 1160.prj (project) ---

Proj Title=Chimney Creek 1160 Base Level Engineering
Current Plan=p01
Default Exp/Contr=0.3,0.1
English Units
Geom File=g01
Flow File=f01
Plan File=p01
BEGIN DESCRIPTION:
Chimney Creek 1160
END DESCRIPTION:

--- Chimney Creek 1160.p01 (plan) ---

Plan Title=Multiple Run
Short Identifier=Multiple
Geom File=g01
Flow File=f01
Subcritical Flow
K Sum by GR= 0
Std Step Tol= 0.01
Critical Tol= 0.01
Num of Std Step Trials= 20
Max Error Tol= 0.3
Flow Tol Ratio= 0.001
Split Flow NTrial= 30
Split Flow Tol= 0.02
Split Flow Ratio= 0.02
Log Output Level= 0
Friction Slope Method= 1
Unsteady Friction Slope Method= 2
Unsteady Bridges Friction Slope Method= 1
Parabolic Critical Depth
Global Vel Dist=  1 , 1 , 1
Global Log Level= 0
CheckData=True
Encroach Param= -1, 0, 0, 0
BEGIN DESCRIPTION:
Multiple Run
END DESCRIPTION:

--- Chimney Creek 1160.f01 (steady flow) ---

Flow Title=Multiple
Number of Profiles=7
Profile Names=10-year,25-year,50-year,1pct_min,100-year,1pct_plu,500-year
River Rch & RM= Chimney Creek 11,Reach-1,10639
     388     547     682     423     845    1686    1311
River Rch & RM= Chimney Creek 11,Reach-1,4039
     587     848    1074     675    1347    2688    2150
Boundary for River Rch & Prof#=Chimney Creek 11,Reach-1,1
Up Type=0
Dn Type=3
Dn Slope=0.005
Boundary for River Rch & Prof#=Chimney Creek 11,Reach-1,2
Up Type=0
Dn Type=3
Dn Slope=0.005
Boundary for River Rch & Prof#=Chimney Creek 11,Reach-1,3
Up Type=0
Dn Type=3
Dn Slope=0.005
Boundary for River Rch & Prof#=Chimney Creek 11,Reach-1,4
Up Type=0
Dn Type=3
Dn Slope=0.005
Boundary for River Rch & Prof#=Chimney Creek 11,Reach-1,5
Up Type=0
Dn Type=3
Dn Slope=0.005
Boundary for River Rch & Prof#=Chimney Creek 11,Reach-1,6
Up Type=0
Dn Type=3
Dn Slope=0.005
Boundary for River Rch & Prof#=Chimney Creek 11,Reach-1,7
Up Type=0
Dn Type=3
Dn Slope=0.005

--- Chimney Creek 1160.g01 (geometry) ---

Geom Title=Existing Conditions

River Reach=Chimney Creek 11,Reach-1
Reach XY= 30
      1673855.00      6979988.00      1673508.22      6980230.13
      1673336.59      6980087.63      1673145.30      6980198.77
      1672557.18      6980983.22      1672497.32      6980731.47
      1672360.90      6980689.97      1672081.41      6980810.84
      1671957.40      6981082.62      1671741.70      6981051.31
      1671607.58      6981332.29      1671384.80      6981438.37
      1671148.81      6981345.75      1671008.75      6981539.55
      1670825.42      6982168.25      1670710.87      6982236.50
      1670552.73      6982093.05      1670091.73      6982401.63
      1670039.31      6982554.78      1669744.56      6982786.95
      1669198.83      6982730.14      1668865.78      6982397.68
      1668722.13      6982104.45      1667898.66      6981629.98
      1667753.51      6981441.45      1667637.90      6981454.32
      1667435.02      6981738.05      1667256.47      6981734.45
      1667044.50      6981589.20      1666555.00      6981538.00

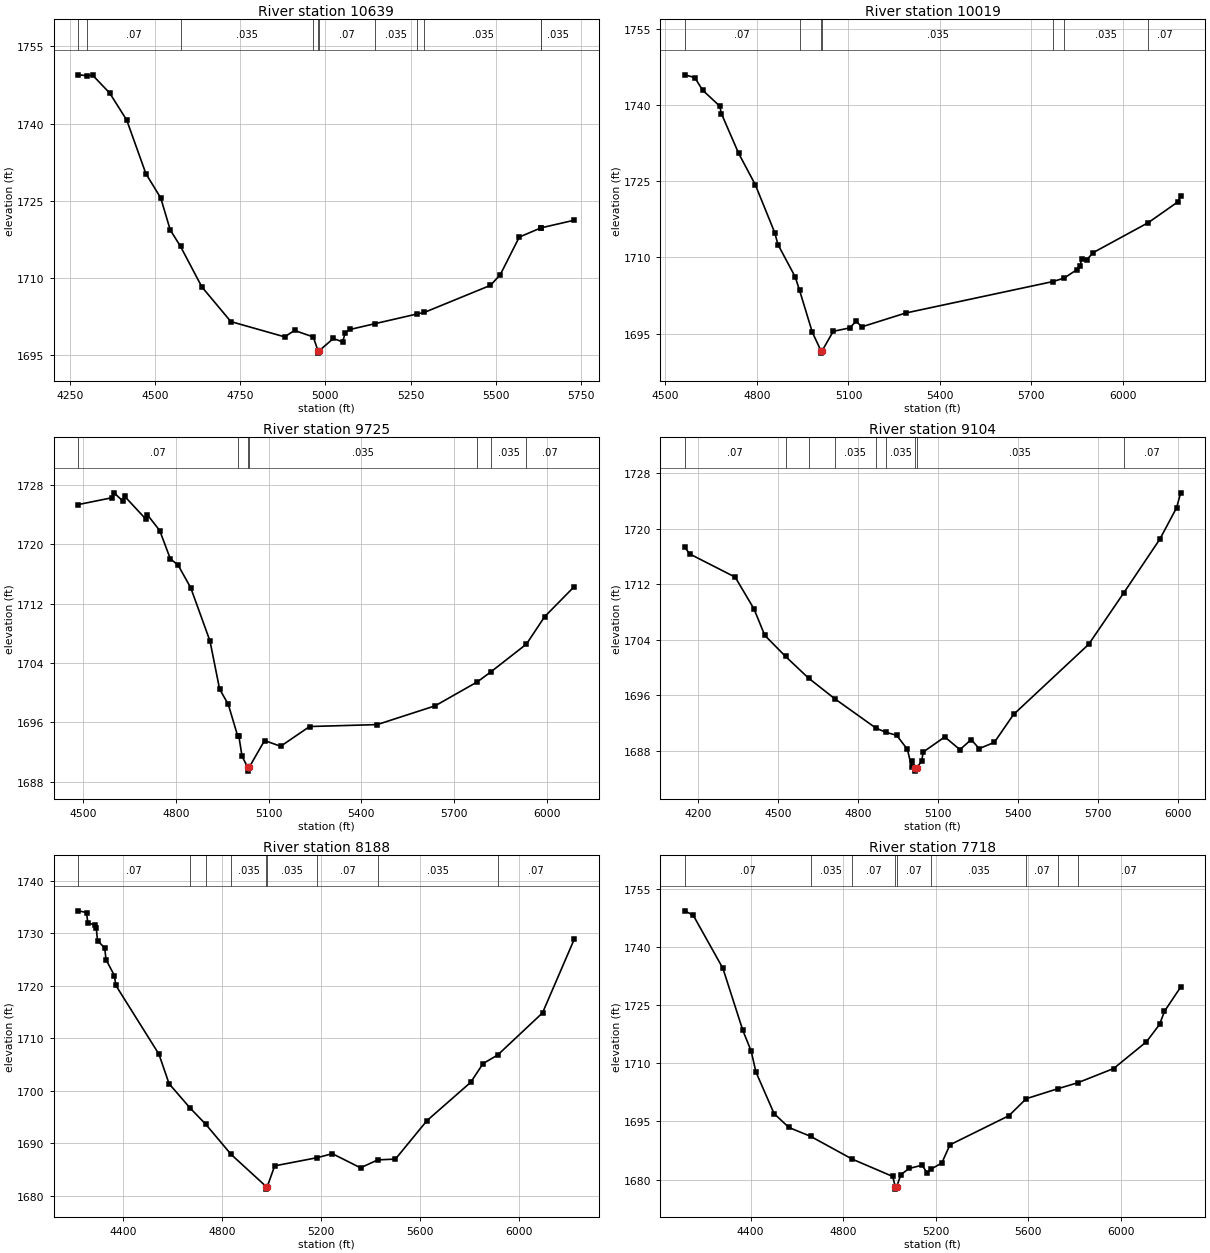
Type RM Length L Ch R = 1,10639,620,620,620
BEGIN DESCRIPTION:
Chimney Creek 1160 19.0
END DESCRIPTION:
XS GIS Cut Line= 3
      1673220.55      6979604.12      1673796.94      6980043.90
      1674359.91      6980509.09
#Sta/Elev= 30
  4275.0 1749.46  4300.1 1749.30  4317.3 1749.37  4367.2 1745.91  4417.1 1740.66
  4473.3 1730.27  4516.9 1725.55  4544.7 1719.35  4574.9 1716.15  4637.5 1708.29
  4722.7 1701.55  4880.6 1698.59  4909.5 1699.83  4964.6 1698.57  4978.2 1695.93
  4978.5 1695.43  4982.6 1695.93  5023.4 1698.27  5050.8 1697.61  5058.6 1699.43
  5073.0 1700.03  5145.6 1701.15  5268.5 1703.02  5290.1 1703.32  5484.6 1708.59
  5513.3 1710.64  5569.2 1717.96  5632.8 1719.75  5634.3 1719.77  5730.3 1721.23
#Mann=11,-1,0
  4275.0   0.035       0  4300.1    0.07       0  4574.9   0.035       0
  4964.6    0.07       0  4978.2    0.07       0  4982.6    0.07       0
  5145.6   0.035       0  5268.5    0.07       0  5290.1   0.035       0
  5632.8    0.07       0  5634.3   0.035       0
Bank Sta=4978.2,4982.6
Exp/Cntr=0.3,0.1

Type RM Length L Ch R = 1,10019,294,294,294
BEGIN DESCRIPTION:
Mapping XS bec8368b
END DESCRIPTION:
XS GIS Cut Line= 3
      1673159.80      6979680.08      1673305.19      6980090.23
      1673751.87      6981193.91
#Sta/Elev= 30
  4563.4 1745.95  4596.1 1745.41  4621.7 1742.94  4677.9 1739.80  4683.5 1738.30
  4739.9 1730.50  4794.6 1724.31  4858.1 1714.91  4868.9 1712.54  4925.2 1706.20
  4939.6 1703.55  4981.6 1695.26  5009.7 1691.67  5010.0 1691.17  5014.1 1691.67
  5050.1 1695.46  5104.0 1696.13  5125.6 1697.48  5143.2 1696.33  5287.4 1699.06
  5770.6 1705.26  5806.7 1705.93  5848.4 1707.56  5859.1 1708.25  5864.5 1709.63
  5880.8 1709.51  5902.3 1710.95  6083.6 1716.87  6180.8 1720.97  6189.2 1722.08
#Mann=7,-1,0
  4563.4    0.07       0  4939.6   0.035       0  5009.7   0.035       0
  5014.1   0.035       0  5770.6    0.07       0  5806.7   0.035       0
  6083.6    0.07       0
Bank Sta=5009.7,5014.1
Exp/Cntr=0.3,0.1

Type RM Length L Ch R = 1,9725,621,621,621
BEGIN DESCRIPTION:
Mapping XS 78296dfa
END DESCRIPTION:
XS GIS Cut Line= 3
      1672940.62      6979766.90      1673077.33      6980263.84
      1673385.50      6981309.89
#Sta/Elev= 30
  4483.5 1725.36  4593.9 1726.29  4599.1 1726.94  4628.3 1725.81  4633.5 1726.47
  4702.3 1723.39  4707.5 1723.96  4747.1 1721.86  4781.5 1718.04  4806.2 1717.23
  4847.6 1714.14  4909.9 1706.97  4941.0 1700.50  4969.1 1698.44  5000.1 1694.11
  5003.6 1694.11  5013.7 1691.44  5032.3 1689.94  5032.6 1689.44  5036.7 1689.94
  5086.6 1693.56  5138.8 1692.79  5232.6 1695.45  5451.5 1695.71  5639.2 1698.24
  5775.9 1701.47  5818.6 1702.78  5934.9 1706.56  5993.6 1710.24  6089.4 1714.29
#Mann=7,-1,0
  4483.5    0.07       0  5000.1   0.035       0  5032.3    0.07       0
  5036.7   0.035       0  5775.9    0.07       0  5818.6   0.035       0
  5934.9    0.07       0
Bank Sta=5032.3,5036.7
Exp/Cntr=0.3,0.1

Type RM Length L Ch R = 1,9104,916,916,916
BEGIN DESCRIPTION:
Mapping XS 239ff86b
END DESCRIPTION:
XS GIS Cut Line= 3
      1672831.95      6979890.89      1672709.56      6980737.22
      1673270.13      6981572.89
#Sta/Elev= 30
  4149.4 1717.33  4167.4 1716.36  4338.5 1713.02  4409.2 1708.44  4449.6 1704.64
  4527.5 1701.61  4613.8 1698.49  4712.3 1695.52  4866.6 1691.30  4904.9 1690.68
  4944.7 1690.26  4985.1 1688.23  5000.9 1685.69  5003.0 1686.53  5015.1 1685.60
  5015.4 1685.10  5019.7 1685.60  5038.4 1686.50  5044.4 1687.85  5125.4 1690.02
  5182.4 1688.19  5224.5 1689.64  5254.5 1688.34  5311.5 1689.24  5383.5 1693.25
  5665.6 1703.35  5797.5 1710.76  5932.7 1718.48  5995.8 1723.01  6010.8 1725.15
#Mann=9,-1,0
  4149.4    0.07       0  4527.5   0.035       0  4613.8    0.07       0
  4712.3   0.035       0  4866.6    0.07       0  4904.9   0.035       0
  5015.1   0.035       0  5019.7   0.035       0  5797.5    0.07       0
Bank Sta=5015.1,5019.7
Exp/Cntr=0.3,0.1

Type RM Length L Ch R = 1,8188,470,470,470
BEGIN DESCRIPTION:
Mapping XS 8b921632
END DESCRIPTION:
XS GIS Cut Line= 3
      1672040.28      6980034.07      1672251.23      6980791.91
      1673059.27      6981703.88
#Sta/Elev= 30
  4219.7 1734.30  4252.8 1733.98  4258.0 1732.03  4286.1 1731.59  4292.2 1730.99
  4297.4 1728.62  4326.5 1727.22  4331.6 1725.01  4365.9 1721.94  4371.0 1720.13
  4545.6 1707.00  4586.7 1701.37  4672.3 1696.71  4735.0 1693.65  4837.3 1687.92
  4979.1 1681.80  4979.4 1681.30  4984.0 1681.80  5013.7 1685.73  5186.6 1687.30
  5247.0 1688.05  5360.8 1685.36  5430.7 1686.87  5502.1 1687.02  5629.2 1694.33
  5806.6 1701.65  5856.2 1705.20  5915.4 1706.84  6096.8 1714.86  6224.8 1728.85
#Mann=9,-1,0
  4219.7    0.07       0  4672.3   0.035       0  4735.0    0.07       0
  4837.3   0.035       0  4979.1   0.035       0  4984.0   0.035       0
  5186.6    0.07       0  5430.7   0.035       0  5915.4    0.07       0
Bank Sta=4979.1,4984
Exp/Cntr=0.3,0.1

Type RM Length L Ch R = 1,7718,758,758,758
BEGIN DESCRIPTION:
Mapping XS 16501f4f
END DESCRIPTION:
XS GIS Cut Line= 3
      1671449.17      6980351.84      1672001.23      6981044.52
      1672904.87      6981916.91
#Sta/Elev= 30
  4115.6 1749.25  4152.2 1748.09  4280.4 1734.40  4366.4 1718.42  4402.1 1713.14
  4422.9 1707.72  4501.4 1696.99  4565.4 1693.42  4658.8 1691.15  4839.2 1685.26
  5013.6 1680.81  5025.3 1678.04  5025.6 1677.54  5030.2 1678.04  5048.8 1681.25
  5084.3 1682.86  5140.9 1683.71  5162.0 1681.70  5181.2 1682.76  5225.8 1684.28
  5261.0 1688.96  5515.7 1696.46  5590.5 1700.84  5726.2 1703.40  5812.8 1704.94
  5968.2 1708.62  6109.7 1715.51  6166.3 1719.96  6187.7 1723.37  6257.4 1729.59
#Mann=9,-1,0
  4115.6    0.07       0  4658.8   0.035       0  4839.2    0.07       0
  5025.3    0.07       0  5030.2    0.07       0  5181.2   0.035       0
  5590.5    0.07       0  5726.2   0.035       0  5812.8    0.07       0
Bank Sta=5025.3,5030.2
Exp/Cntr=0.3,0.1

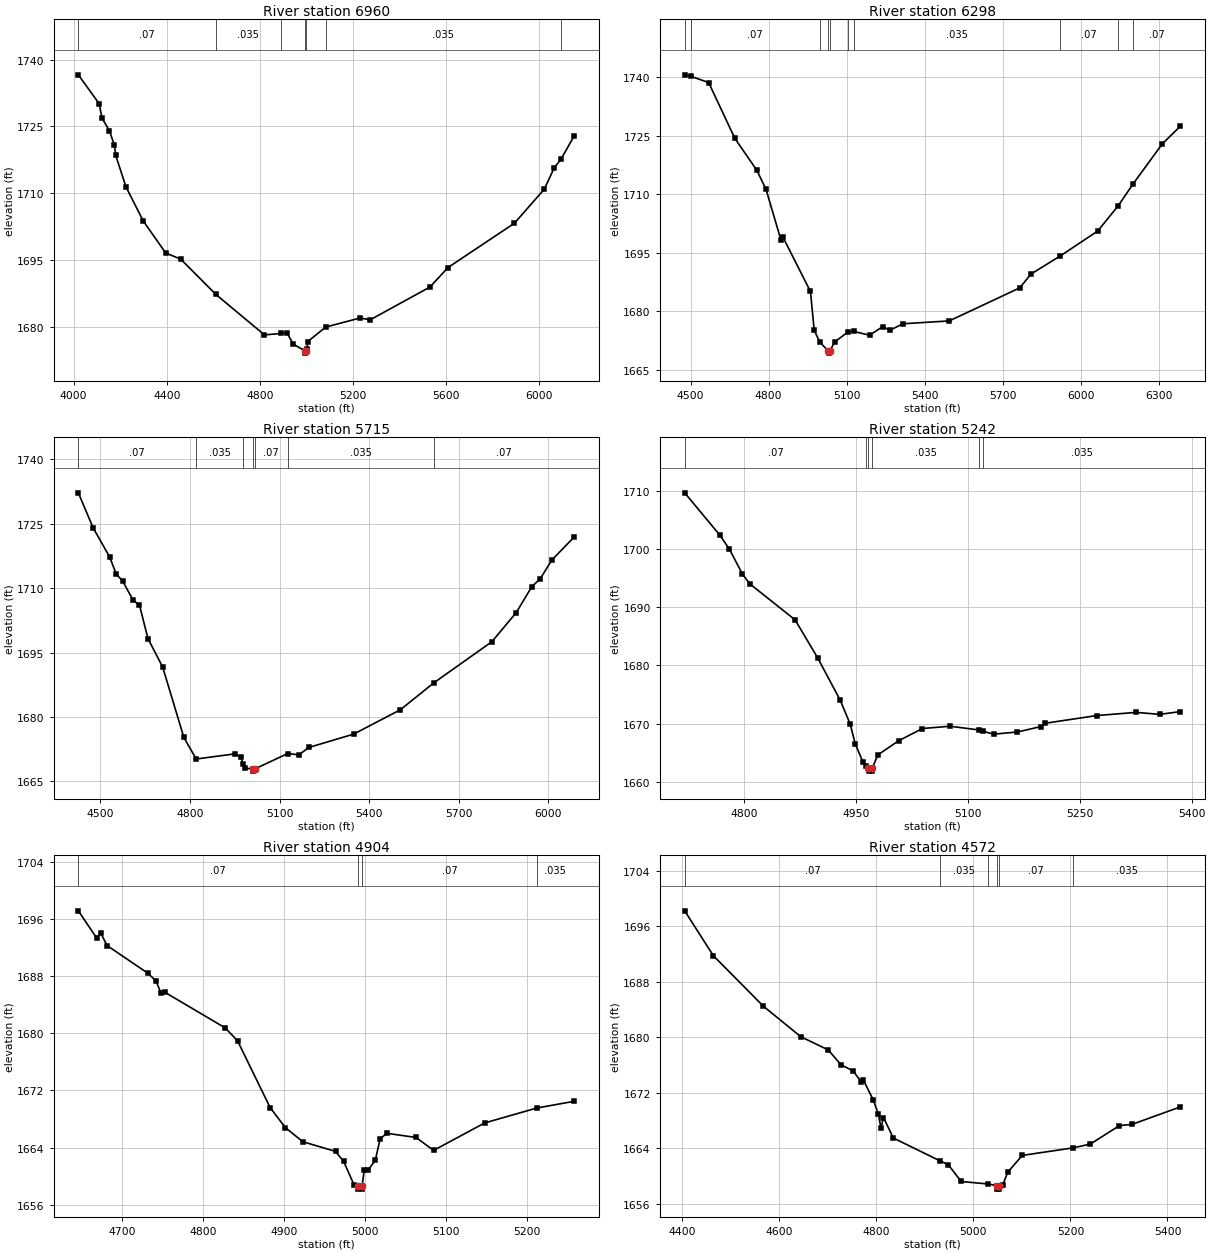
Type RM Length L Ch R = 1,6960,662,662,662
BEGIN DESCRIPTION:
Mapping XS 947a39e6
END DESCRIPTION:
XS GIS Cut Line= 3
      1671021.85      6980530.42      1671512.30      6981385.44
      1672219.43      6982283.46
#Sta/Elev= 30
  4020.0 1736.57  4109.4 1730.11  4121.7 1726.85  4153.4 1724.08  4174.9 1720.77
  4180.7 1718.51  4224.7 1711.47  4298.6 1703.86  4395.0 1696.68  4459.7 1695.30
  4610.7 1687.39  4819.3 1678.33  4888.8 1678.65  4915.7 1678.80  4943.0 1676.25
  4993.6 1674.75  4994.0 1674.25  4998.8 1674.75  5002.0 1675.23  5004.3 1676.80
  5081.9 1680.08  5230.0 1682.12  5273.3 1681.71  5529.9 1689.05  5607.2 1693.41
  5892.3 1703.33  6020.6 1710.94  6063.9 1715.78  6092.5 1717.68  6148.7 1722.85
#Mann=7,-1,0
  4020.0    0.07       0  4610.7   0.035       0  4888.8    0.07       0
  4993.6    0.07       0  4998.8    0.07       0  5081.9   0.035       0
  6092.5    0.07       0
Bank Sta=4993.6,4998.8
Exp/Cntr=0.3,0.1

Type RM Length L Ch R = 1,6298,583,583,583
BEGIN DESCRIPTION:
Mapping XS aa90a049
END DESCRIPTION:
XS GIS Cut Line= 3
      1670605.15      6981207.47      1671013.16      6981541.69
      1672093.90      6982396.73
#Sta/Elev= 30
  4477.6 1740.60  4500.7 1740.24  4569.8 1738.61  4670.3 1724.33  4755.0 1716.15
  4790.1 1711.29  4847.5 1698.32  4854.0 1699.19  4961.0 1685.12  4975.3 1675.21
  4996.6 1672.18  5030.2 1669.83  5030.6 1669.33  5035.5 1669.83  5053.7 1672.19
  5106.2 1674.79  5128.5 1674.88  5188.3 1673.91  5238.0 1676.09  5266.9 1675.22
  5316.6 1676.85  5494.5 1677.58  5765.4 1686.04  5808.7 1689.59  5920.1 1694.17
  6065.1 1700.59  6142.9 1706.98  6202.0 1712.74  6313.5 1722.93  6383.1 1727.46
#Mann=10,-1,0
  4477.6   0.035       0  4500.7    0.07       0  4996.6   0.035       0
  5030.2   0.035       0  5035.5   0.035       0  5106.2    0.07       0
  5128.5   0.035       0  5920.1    0.07       0  6142.9   0.035       0
  6202.0    0.07       0
Bank Sta=5030.2,5035.5
Exp/Cntr=0.3,0.1

Type RM Length L Ch R = 1,5715,473,473,473
BEGIN DESCRIPTION:
Mapping XS f70bd0a2
END DESCRIPTION:
XS GIS Cut Line= 3
      1670483.62      6981650.17      1670865.60      6982075.55
      1671837.78      6982565.98
#Sta/Elev= 30
  4426.0 1732.22  4475.3 1724.11  4531.3 1717.23  4553.0 1713.29  4574.0 1711.74
  4609.8 1707.18  4630.8 1706.10  4659.2 1698.28  4708.5 1691.66  4779.5 1675.25
  4820.9 1670.23  4949.2 1671.42  4970.9 1670.64  4977.7 1669.11  4985.1 1668.12
  5011.4 1667.91  5011.8 1667.41  5016.8 1667.91  5127.6 1671.51  5164.6 1671.21
  5198.7 1672.93  5348.6 1676.04  5504.7 1681.70  5616.1 1687.93  5811.3 1697.55
  5893.1 1704.35  5945.1 1710.37  5973.0 1712.18  6012.0 1716.55  6086.6 1721.91
#Mann=7,-1,0
  4426.0    0.07       0  4820.9   0.035       0  4977.7    0.07       0
  5011.4    0.07       0  5016.8    0.07       0  5127.6   0.035       0
  5616.1    0.07       0
Bank Sta=5011.4,5016.8
Exp/Cntr=0.3,0.1

Type RM Length L Ch R = 1,5242,338,338,338
BEGIN DESCRIPTION:
Mapping XS d6e8af30
END DESCRIPTION:
XS GIS Cut Line= 3
      1670532.87      6981811.23      1670567.60      6982090.75
      1670687.01      6982454.17
#Sta/Elev= 30
  4720.8 1709.65  4767.9 1702.38  4780.8 1699.96  4798.2 1695.68  4808.2 1694.00
  4868.7 1687.83  4898.9 1681.32  4929.2 1674.02  4942.6 1669.90  4949.3 1666.53
  4959.4 1663.49  4964.3 1662.74  4966.8 1662.35  4967.2 1661.85  4971.8 1661.85
  4972.2 1662.35  4979.5 1664.63  5007.5 1667.07  5039.3 1669.17  5076.4 1669.56
  5114.6 1668.93  5121.0 1668.68  5134.7 1668.20  5166.5 1668.57  5198.3 1669.51
  5203.6 1670.07  5273.2 1671.40  5325.6 1671.94  5357.4 1671.60  5385.0 1672.08
#Mann=6,-1,0
  4720.8    0.07       0  4964.3   0.035       0  4966.8   0.035       0
  4972.2   0.035       0  5114.6    0.07       0  5121.0   0.035       0
Bank Sta=4966.8,4972.2
Exp/Cntr=0.3,0.1

Type RM Length L Ch R = 1,4904,332,332,332
BEGIN DESCRIPTION:
Mapping XS 007623e2
END DESCRIPTION:
XS GIS Cut Line= 3
      1670256.84      6981932.79      1670301.97      6982283.46
      1670517.24      6982427.55
#Sta/Elev= 30
  4645.5 1697.14  4668.1 1693.34  4673.1 1694.05  4681.0 1692.28  4731.4 1688.41
  4741.5 1687.32  4747.6 1685.64  4752.6 1685.73  4827.1 1680.75  4842.3 1678.94
  4882.6 1669.58  4901.5 1666.78  4923.0 1664.82  4963.3 1663.47  4973.4 1662.06
  4986.1 1658.81  4990.8 1658.69  4991.3 1658.19  4995.9 1658.19  4996.3 1658.69
  4998.8 1660.90  5003.9 1660.90  5012.5 1662.24  5018.5 1665.25  5026.8 1666.00
  5062.9 1665.42  5084.5 1663.61  5147.6 1667.45  5212.0 1669.54  5258.1 1670.48
#Mann=4,-1,0
  4645.5    0.07       0  4990.8    0.07       0  4996.3    0.07       0
  5212.0   0.035       0
Bank Sta=4990.8,4996.3
Exp/Cntr=0.3,0.1

Type RM Length L Ch R = 1,4572,533,533,533
BEGIN DESCRIPTION:
Chimney Creek 1160 8.0
END DESCRIPTION:
XS GIS Cut Line= 3
      1670177.88      6981880.88      1670034.07      6982457.93
      1670460.72      6982464.52
#Sta/Elev= 30
  4405.3 1698.20  4464.2 1691.75  4567.2 1684.47  4644.6 1680.06  4701.2 1678.16
  4727.2 1676.03  4752.7 1675.12  4768.4 1673.61  4773.6 1673.80  4794.0 1670.93
  4804.3 1668.91  4809.7 1666.91  4814.9 1668.42  4835.2 1665.47  4932.0 1662.16
  4948.5 1661.62  4974.9 1659.21  5030.4 1658.85  5048.2 1658.61  5048.6 1658.11
  5053.2 1658.11  5053.7 1658.61  5060.9 1658.75  5070.9 1660.55  5100.9 1662.97
  5204.5 1664.04  5241.0 1664.60  5301.0 1667.26  5327.1 1667.44  5426.7 1669.96
#Mann=6,-1,0
  4405.3    0.07       0  4932.0   0.035       0  5030.4    0.07       0
  5048.2   0.035       0  5053.7    0.07       0  5204.5   0.035       0
Bank Sta=5048.2,5053.7
Exp/Cntr=0.3,0.1

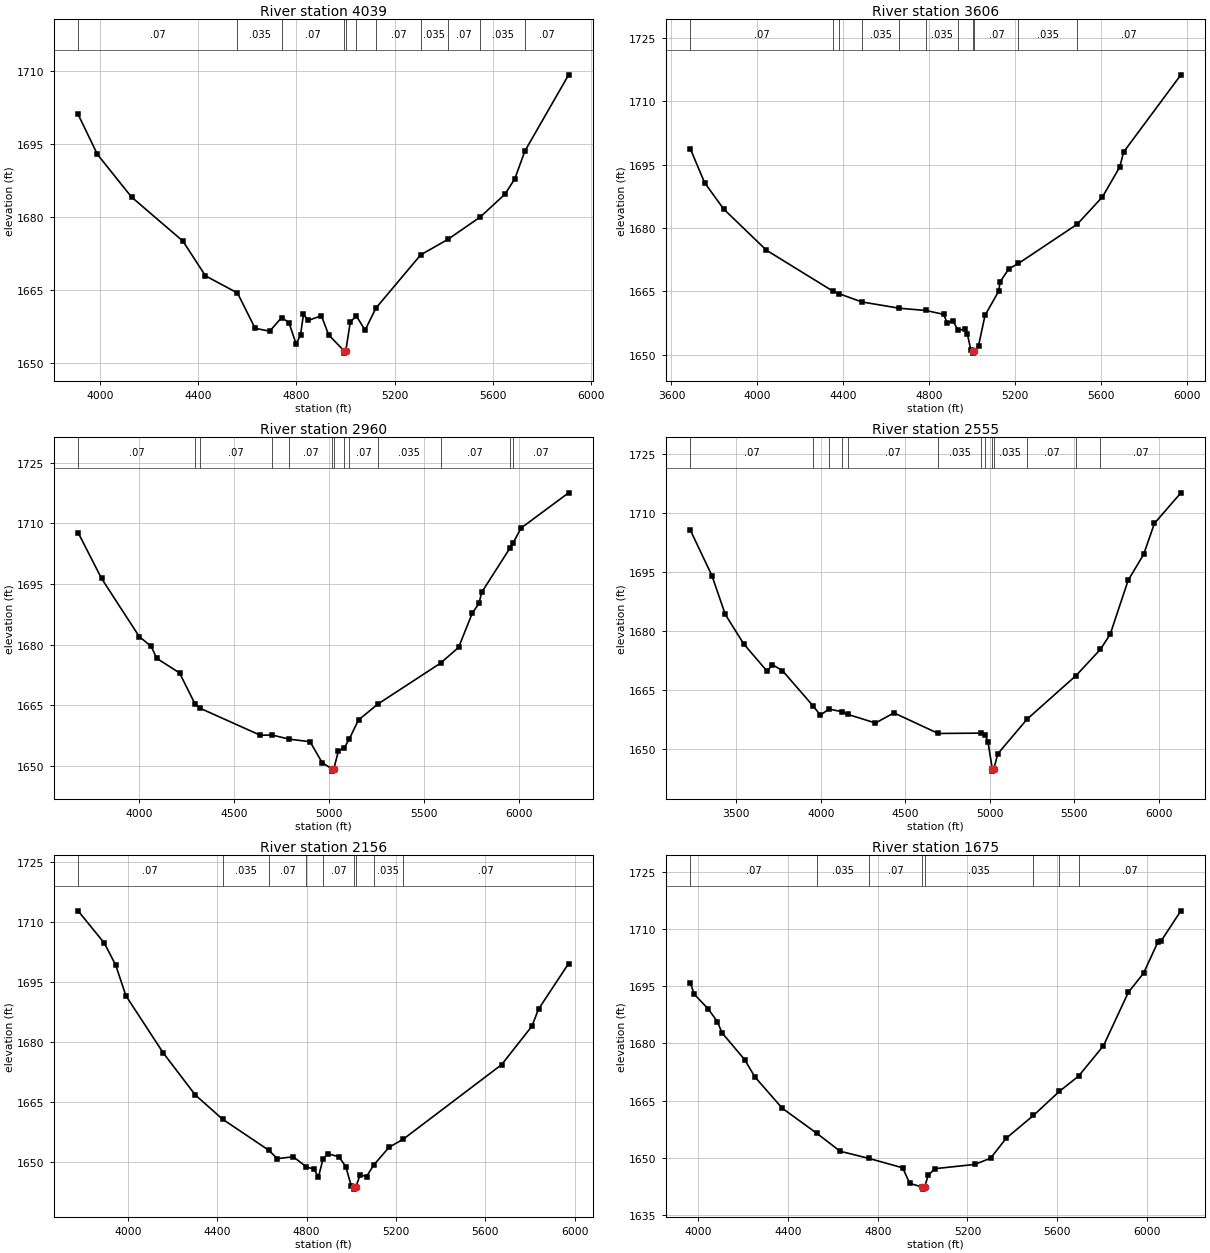
Type RM Length L Ch R = 1,4039,433,433,433
BEGIN DESCRIPTION:
Chimney Creek 1160 7.0
END DESCRIPTION:
XS GIS Cut Line= 3
      1670117.50      6981775.67      1669715.21      6982788.50
      1669734.18      6983697.20
#Sta/Elev= 30
  3910.2 1701.06  3989.1 1692.83  4127.9 1684.10  4337.3 1675.06  4429.2 1667.94
  4559.7 1664.42  4631.5 1657.18  4690.9 1656.59  4739.6 1659.38  4769.2 1658.34
  4798.9 1653.95  4816.5 1655.82  4828.6 1660.05  4847.5 1658.78  4901.5 1659.76
  4931.2 1655.83  4993.1 1652.59  4993.6 1652.09  5001.0 1652.59  5019.5 1658.52
  5044.3 1659.69  5079.5 1656.81  5124.1 1661.34  5306.0 1672.23  5416.2 1675.39
  5549.1 1680.01  5649.6 1684.68  5689.7 1687.83  5730.5 1693.51  5908.9 1709.15
#Mann=11,-1,0
  3910.2    0.07       0  4559.7   0.035       0  4739.6    0.07       0
  4993.1    0.07       0  5001.0    0.07       0  5044.3   0.035       0
  5124.1    0.07       0  5306.0   0.035       0  5416.2    0.07       0
  5549.1   0.035       0  5730.5    0.07       0
Bank Sta=4993.1,5001
Exp/Cntr=0.3,0.1

Type RM Length L Ch R = 1,3606,646,646,646
BEGIN DESCRIPTION:
Mapping XS 62439818
END DESCRIPTION:
XS GIS Cut Line= 3
      1669900.85      6981574.76      1669294.07      6982746.64
      1669174.28      6983702.41
#Sta/Elev= 30
  3687.8 1698.77  3754.1 1690.75  3842.7 1684.50  4041.9 1674.73  4350.9 1665.03
  4378.3 1664.44  4485.4 1662.47  4660.6 1660.97  4784.3 1660.44  4866.2 1659.52
  4882.7 1657.58  4910.4 1657.90  4934.4 1655.73  4963.9 1656.03  4976.8 1654.93
  4993.3 1651.04  5001.4 1650.83  5001.9 1650.33  5009.5 1650.83  5029.0 1652.08
  5059.2 1659.28  5122.7 1665.02  5129.8 1667.28  5170.1 1670.31  5214.6 1671.58
  5488.5 1680.90  5605.8 1687.37  5686.3 1694.45  5704.2 1698.00  5970.7 1716.30
#Mann=11,-1,0
  3687.8    0.07       0  4350.9   0.035       0  4378.3    0.07       0
  4485.4   0.035       0  4660.6    0.07       0  4784.3   0.035       0
  4934.4    0.07       0  5001.4    0.07       0  5009.5    0.07       0
  5214.6   0.035       0  5488.5    0.07       0
Bank Sta=5001.4,5009.5
Exp/Cntr=0.3,0.1

Type RM Length L Ch R = 1,2960,405,405,405
BEGIN DESCRIPTION:
Mapping XS f64ab89e
END DESCRIPTION:
XS GIS Cut Line= 3
      1669765.42      6981384.02      1668836.61      6982334.53
      1667864.40      6983120.12
#Sta/Elev= 30
  3680.9 1707.76  3804.2 1696.41  4002.2 1682.03  4065.8 1679.56  4094.1 1676.64
  4214.4 1673.01  4296.3 1665.28  4323.9 1664.24  4638.6 1657.60  4701.1 1657.64
  4791.8 1656.62  4900.4 1655.99  4963.9 1650.83  5016.6 1649.21  5017.1 1648.71
  5025.0 1649.21  5049.6 1653.71  5079.3 1654.35  5107.5 1656.74  5155.2 1661.38
  5258.2 1665.35  5586.3 1675.43  5681.3 1679.33  5753.2 1687.80  5788.4 1690.22
  5802.8 1692.96  5952.1 1703.97  5967.3 1705.10  6009.1 1708.85  6259.8 1717.59
#Mann=13,-1,0
  3680.9    0.07       0  4296.3   0.035       0  4323.9    0.07       0
  4701.1   0.035       0  4791.8    0.07       0  5016.6    0.07       0
  5025.0    0.07       0  5079.3   0.035       0  5107.5    0.07       0
  5258.2   0.035       0  5586.3    0.07       0  5952.1   0.035       0
  5967.3    0.07       0
Bank Sta=5016.6,5025
Exp/Cntr=0.3,0.1

Type RM Length L Ch R = 1,2555,399,399,399
BEGIN DESCRIPTION:
Mapping XS 7598d2f9
END DESCRIPTION:
XS GIS Cut Line= 3
      1669244.58      6980390.13      1668602.23      6982052.41
      1667825.31      6982859.72
#Sta/Elev= 30
  3227.6 1705.69  3355.3 1694.11  3434.4 1684.22  3543.5 1676.71  3682.6 1669.72
  3712.5 1671.43  3772.4 1669.91  3954.5 1660.89  3997.2 1658.56  4047.7 1660.12
  4124.3 1659.45  4159.0 1658.77  4323.2 1656.56  4432.3 1659.14  4694.3 1653.90
  4945.5 1653.99  4973.3 1653.41  4988.5 1651.81  5014.4 1644.81  5014.9 1644.31
  5022.8 1644.81  5046.9 1648.73  5220.0 1657.54  5509.9 1668.65  5653.6 1675.30
  5711.7 1679.15  5818.0 1692.90  5909.8 1699.52  5973.6 1707.41  6130.1 1715.19
#Mann=13,-1,0
  3227.6    0.07       0  3954.5   0.035       0  4047.7    0.07       0
  4124.3   0.035       0  4159.0    0.07       0  4694.3   0.035       0
  4945.5    0.07       0  4973.3   0.035       0  5014.4   0.035       0
  5022.8   0.035       0  5220.0    0.07       0  5509.9   0.035       0
  5653.6    0.07       0
Bank Sta=5014.4,5022.8
Exp/Cntr=0.3,0.1

Type RM Length L Ch R = 1,2156,481,481,481
BEGIN DESCRIPTION:
Mapping XS a4d7a2df
END DESCRIPTION:
XS GIS Cut Line= 3
      1668532.79      6980624.47      1668285.39      6981844.08
      1667743.66      6982624.18
#Sta/Elev= 30
  3778.0 1712.77  3895.8 1704.66  3946.4 1699.16  3992.0 1691.51  4159.1 1677.18
  4302.0 1666.69  4424.1 1660.61  4630.7 1652.84  4669.3 1650.72  4740.7 1651.19
  4799.0 1648.65  4832.6 1648.11  4853.2 1646.12  4873.3 1650.58  4893.7 1651.94
  4944.3 1651.23  4975.4 1648.74  5000.1 1643.86  5012.0 1643.59  5012.5 1643.09
  5020.4 1643.59  5039.4 1646.68  5068.4 1646.23  5099.8 1649.09  5169.7 1653.60
  5232.4 1655.59  5672.5 1674.26  5807.9 1683.88  5837.6 1688.17  5972.2 1699.58
#Mann=9,-1,0
  3778.0    0.07       0  4424.1   0.035       0  4630.7    0.07       0
  4799.0   0.035       0  4873.3    0.07       0  5012.0    0.07       0
  5020.4    0.07       0  5099.8   0.035       0  5232.4    0.07       0
Bank Sta=5012,5020.4
Exp/Cntr=0.3,0.1

Type RM Length L Ch R = 1,1675,827,827,827
BEGIN DESCRIPTION:
Mapping XS 47a48a11
END DESCRIPTION:
XS GIS Cut Line= 3
      1668142.15      6980611.49      1667877.41      6981622.73
      1667478.42      6982693.92
#Sta/Elev= 30
  3964.0 1695.90  3981.1 1692.91  4043.1 1689.08  4084.4 1685.73  4105.1 1682.80
  4206.4 1675.74  4251.9 1671.23  4373.9 1663.03  4527.8 1656.47  4632.3 1651.75
  4759.9 1649.89  4911.4 1647.41  4942.4 1643.37  4999.6 1642.33  5000.1 1641.83
  5009.0 1642.33  5025.4 1645.52  5055.7 1647.19  5232.4 1648.30  5303.1 1649.91
  5373.4 1655.18  5494.7 1661.13  5610.5 1667.45  5695.9 1671.43  5807.0 1679.39
  5917.7 1693.34  5986.0 1698.41  6050.0 1706.58  6064.0 1706.82  6152.4 1714.73
#Mann=8,-1,0
  3964.0    0.07       0  4527.8   0.035       0  4759.9    0.07       0
  4999.6    0.07       0  5009.0   0.035       0  5494.7    0.07       0
  5610.5   0.035       0  5695.9    0.07       0
Bank Sta=4999.6,5009
Exp/Cntr=0.3,0.1

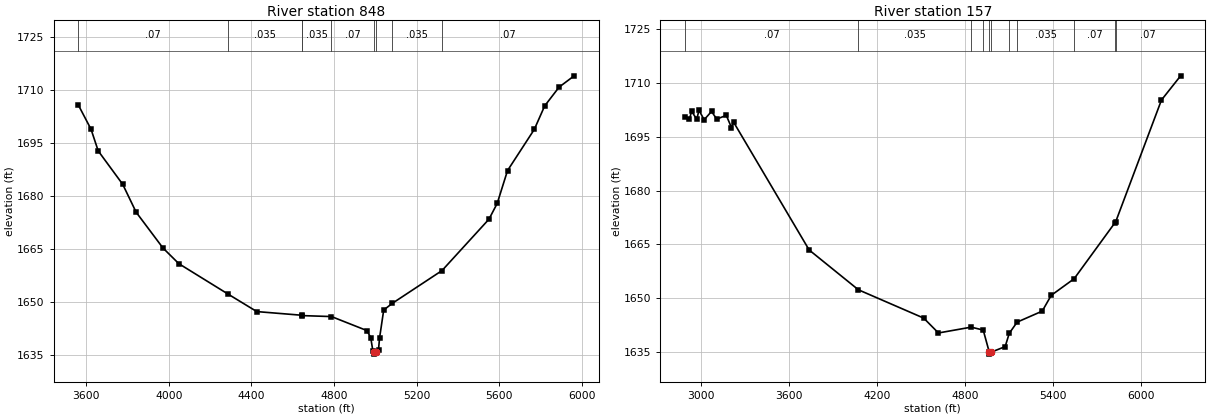
Type RM Length L Ch R = 1,848,691,691,691
BEGIN DESCRIPTION:
Mapping XS c12503fa
END DESCRIPTION:
XS GIS Cut Line= 3
      1667884.86      6980409.18      1667327.58      6981752.91
      1667317.16      6982700.85
#Sta/Elev= 30
  3561.2 1705.78  3622.8 1698.92  3657.5 1692.80  3776.4 1683.34  3841.4 1675.46
  3971.3 1665.35  4048.1 1660.92  4284.1 1652.41  4426.0 1647.37  4644.6 1646.33
  4646.6 1646.23  4787.9 1645.96  4959.6 1642.00  4978.1 1640.01  4988.9 1636.11
  4995.0 1635.84  4995.5 1635.34  5004.5 1635.84  5015.9 1636.64  5021.0 1639.94
  5041.0 1647.81  5082.7 1649.70  5323.6 1658.97  5551.0 1673.49  5591.0 1677.96
  5641.0 1687.24  5771.0 1698.91  5821.0 1705.52  5891.0 1710.84  5963.9 1714.03
#Mann=9,-1,0
  3561.2    0.07       0  4284.1   0.035       0  4644.6    0.07       0
  4646.6   0.035       0  4787.9    0.07       0  4995.0    0.07       0
  5004.5    0.07       0  5082.7   0.035       0  5323.6    0.07       0
Bank Sta=4995,5004.5
Exp/Cntr=0.3,0.1

Type RM Length L Ch R = 1,157,0,0,0
BEGIN DESCRIPTION:
Chimney Creek 1160 1.0
END DESCRIPTION:
XS GIS Cut Line= 3
      1667937.31      6979885.89      1666695.72      6981588.46
      1667180.01      6982763.03
#Sta/Elev= 30
  2892.8 1700.58  2924.3 1699.80  2938.9 1702.08  2974.5 1699.84  2989.2 1702.36
  3024.7 1699.72  3074.9 1702.03  3110.4 1699.89  3175.3 1700.94  3210.9 1697.53
  3225.5 1699.02  3740.0 1663.46  4075.4 1652.38  4520.2 1644.50  4620.7 1640.36
  4843.7 1641.98  4925.7 1641.17  4967.3 1634.97  4967.8 1634.47  4976.9 1634.97
  5075.2 1636.56  5103.3 1640.28  5156.8 1643.38  5327.7 1646.44  5388.9 1650.83
  5545.2 1655.46  5822.5 1671.01  5828.5 1671.34  6140.0 1705.21  6270.5 1711.94
#Mann=11,-1,0
  2892.8    0.07       0  4075.4   0.035       0  4843.7    0.07       0
  4925.7   0.035       0  4967.3   0.035       0  4976.9   0.035       0
  5103.3    0.07       0  5156.8   0.035       0  5545.2    0.07       0
  5822.5   0.035       0  5828.5    0.07       0
Bank Sta=4967.3,4976.9
Exp/Cntr=0.3,0.1

Chan Stop Cuts=-1