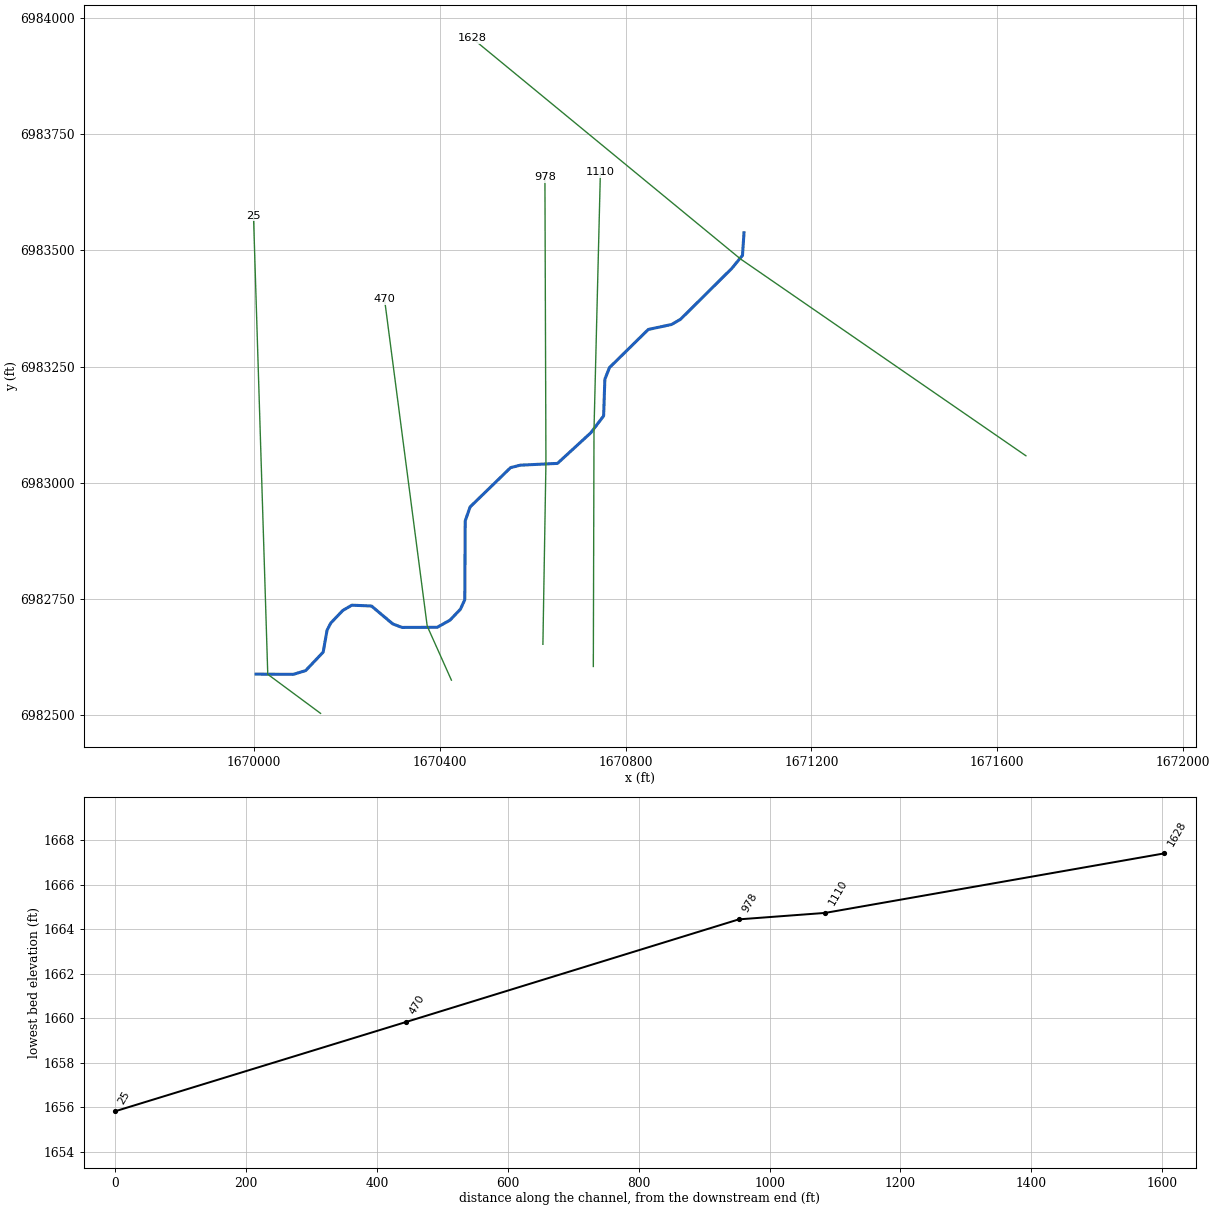
--- Chimney Creek 1161.prj (project) ---

Proj Title=Chimney Creek 1161 Base Level Engineering
Current Plan=p01
Default Exp/Contr=0.3,0.1
English Units
Geom File=g01
Flow File=f01
Plan File=p01
BEGIN DESCRIPTION:
Chimney Creek 1161
END DESCRIPTION:

--- Chimney Creek 1161.p01 (plan) ---

Plan Title=Multiple Run
Short Identifier=Multiple
Geom File=g01
Flow File=f01
Subcritical Flow
K Sum by GR= 0
Std Step Tol= 0.01
Critical Tol= 0.01
Num of Std Step Trials= 20
Max Error Tol= 0.3
Flow Tol Ratio= 0.001
Split Flow NTrial= 30
Split Flow Tol= 0.02
Split Flow Ratio= 0.02
Log Output Level= 0
Friction Slope Method= 1
Unsteady Friction Slope Method= 2
Unsteady Bridges Friction Slope Method= 1
Parabolic Critical Depth
Global Vel Dist=  1 , 1 , 1
Global Log Level= 0
CheckData=True
Encroach Param= -1, 0, 0, 0
BEGIN DESCRIPTION:
Multiple Run
END DESCRIPTION:

--- Chimney Creek 1161.f01 (steady flow) ---

Flow Title=Multiple
Number of Profiles=7
Profile Names=10-year,25-year,50-year,1pct_min,100-year,1pct_plu,500-year
River Rch & RM= Chimney Creek 11,Reach-1,1628
     258     357     439     269     536    1069     810
River Rch & RM= Chimney Creek 11,Reach-1,25
     587     848    1074     675    1347    2688    2150
Boundary for River Rch & Prof#=Chimney Creek 11,Reach-1,1
Up Type=0
Dn Type=3
Dn Slope=0.005
Boundary for River Rch & Prof#=Chimney Creek 11,Reach-1,2
Up Type=0
Dn Type=3
Dn Slope=0.005
Boundary for River Rch & Prof#=Chimney Creek 11,Reach-1,3
Up Type=0
Dn Type=3
Dn Slope=0.005
Boundary for River Rch & Prof#=Chimney Creek 11,Reach-1,4
Up Type=0
Dn Type=3
Dn Slope=0.005
Boundary for River Rch & Prof#=Chimney Creek 11,Reach-1,5
Up Type=0
Dn Type=3
Dn Slope=0.005
Boundary for River Rch & Prof#=Chimney Creek 11,Reach-1,6
Up Type=0
Dn Type=3
Dn Slope=0.005
Boundary for River Rch & Prof#=Chimney Creek 11,Reach-1,7
Up Type=0
Dn Type=3
Dn Slope=0.005

--- Chimney Creek 1161.g01 (geometry) ---

Geom Title=Existing Conditions

River Reach=Chimney Creek 11,Reach-1
Reach XY= 30
      1671055.00      6983538.00      1671051.73      6983489.35
      1671028.65      6983461.20      1670918.21      6983351.63
      1670898.95      6983340.54      1670848.93      6983329.85
      1670765.51      6983247.81      1670755.52      6983222.79
      1670752.85      6983143.88      1670725.51      6983107.72
      1670653.51      6983041.61      1670573.28      6983037.75
      1670552.56      6983032.48      1670465.47      6982947.83
      1670454.96      6982918.02      1670454.02      6982748.26
      1670444.68      6982727.81      1670422.22      6982704.21
      1670394.69      6982688.86      1670318.97      6982688.56
      1670298.95      6982696.14      1670253.22      6982734.67
      1670210.85      6982736.46      1670191.44      6982725.02
      1670165.65      6982698.10      1670157.58      6982682.56
      1670149.26      6982635.46      1670111.54      6982595.60
      1670085.27      6982587.62      1670005.00      6982588.00

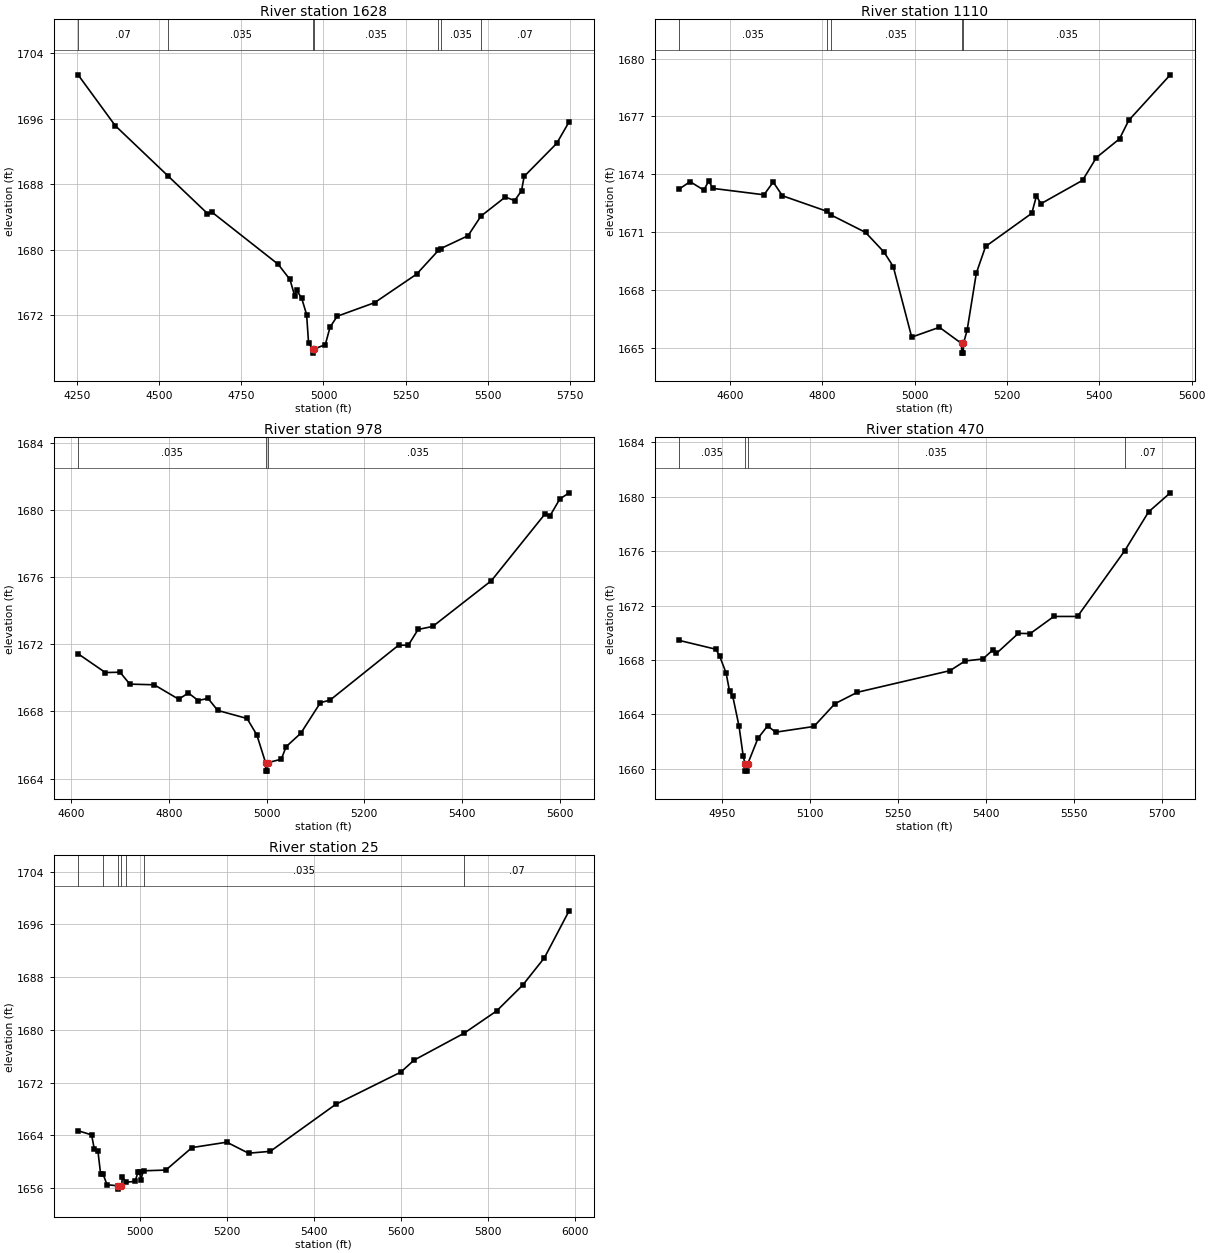
Type RM Length L Ch R = 1,1628,518,518,518
BEGIN DESCRIPTION:
Chimney Creek 1161 3.0
END DESCRIPTION:
XS GIS Cut Line= 3
      1671661.69      6983058.03      1671047.24      6983481.79
      1670470.30      6983956.45
#Sta/Elev= 30
  4253.6 1701.37  4366.5 1695.17  4527.6 1689.01  4647.1 1684.44  4662.0 1684.57
  4862.1 1678.25  4898.0 1676.39  4912.8 1674.35  4918.9 1675.06  4933.8 1674.09
  4948.7 1672.11  4954.7 1668.61  4967.6 1667.90  4967.9 1667.40  4971.6 1667.90
  5005.6 1668.44  5020.0 1670.57  5041.7 1671.90  5155.6 1673.56  5283.3 1677.04
  5349.8 1679.95  5357.2 1680.17  5439.7 1681.73  5478.9 1684.12  5553.0 1686.45
  5581.7 1686.02  5602.5 1687.23  5610.4 1688.97  5709.4 1693.00  5747.1 1695.63
#Mann=7,-1,0
  4253.6    0.07       0  4527.6   0.035       0  4967.6   0.035       0
  4971.6   0.035       0  5349.8    0.07       0  5357.2   0.035       0
  5478.9    0.07       0
Bank Sta=4967.6,4971.6
Exp/Cntr=0.3,0.1

Type RM Length L Ch R = 1,1110,132,132,132
BEGIN DESCRIPTION:
Chimney Creek 1161 2.0
END DESCRIPTION:
XS GIS Cut Line= 3
      1670730.69      6982604.52      1670732.15      6983114.42
      1670745.88      6983667.85
#Sta/Elev= 30
  4490.1 1673.24  4513.6 1673.62  4543.6 1673.18  4553.6 1673.65  4563.6 1673.27
  4673.6 1672.94  4693.6 1673.60  4713.6 1672.89  4810.4 1672.08  4818.3 1671.90
  4893.6 1670.99  4933.6 1669.97  4953.6 1669.22  4993.6 1665.56  5053.6 1666.07
  5101.6 1665.23  5101.9 1664.73  5105.4 1664.73  5105.6 1665.23  5113.6 1665.91
  5133.6 1668.88  5153.6 1670.26  5253.7 1671.98  5263.7 1672.87  5273.7 1672.48
  5363.7 1673.69  5393.7 1674.87  5443.7 1675.84  5463.7 1676.80  5553.6 1679.16
#Mann=5,-1,0
  4490.1   0.035       0  4810.4    0.07       0  4818.3   0.035       0
  5101.6   0.035       0  5105.6   0.035       0
Bank Sta=5101.6,5105.6
Exp/Cntr=0.3,0.1

Type RM Length L Ch R = 1,978,508,508,508
BEGIN DESCRIPTION:
Mapping XS c0855660
END DESCRIPTION:
XS GIS Cut Line= 3
      1670622.18      6982652.25      1670628.69      6983042.85
      1670626.52      6983656.99
#Sta/Elev= 30
  4614.3 1671.44  4670.1 1670.32  4700.1 1670.34  4720.1 1669.63  4770.1 1669.59
  4820.1 1668.73  4840.1 1669.10  4860.1 1668.65  4880.1 1668.78  4900.1 1668.06
  4960.1 1667.58  4980.1 1666.60  4998.0 1664.94  4998.3 1664.44  5001.8 1664.44
  5002.0 1664.94  5030.1 1665.15  5040.1 1665.90  5070.1 1666.70  5110.1 1668.52
  5130.1 1668.68  5270.1 1671.95  5290.1 1671.95  5310.1 1672.89  5340.1 1673.07
  5460.1 1675.80  5570.1 1679.79  5580.1 1679.67  5600.1 1680.67  5619.1 1681.04
#Mann=3,-1,0
  4614.3   0.035       0  4998.0   0.035       0  5002.0   0.035       0
Bank Sta=4998,5002
Exp/Cntr=0.3,0.1

Type RM Length L Ch R = 1,470,445,445,445
BEGIN DESCRIPTION:
Mapping XS 6f6372bf
END DESCRIPTION:
XS GIS Cut Line= 3
      1670425.23      6982575.13      1670373.15      6982691.44
      1670281.36      6983394.63
#Sta/Elev= 30
  4877.1 1669.44  4939.7 1668.79  4946.0 1668.28  4956.9 1667.05  4962.9 1665.69
  4968.3 1665.33  4978.9 1663.16  4986.1 1660.94  4989.5 1660.34  4989.8 1659.84
  4993.3 1659.84  4993.5 1660.34  5011.2 1662.25  5027.6 1663.16  5041.4 1662.70
  5106.6 1663.12  5142.3 1664.79  5180.5 1665.63  5338.4 1667.22  5364.1 1667.93
  5394.4 1668.08  5412.3 1668.77  5417.4 1668.48  5454.9 1669.96  5475.1 1669.94
  5515.4 1671.20  5555.7 1671.20  5636.2 1676.03  5676.8 1678.88  5713.7 1680.28
#Mann=4,-1,0
  4877.1   0.035       0  4989.5   0.035       0  4993.5   0.035       0
  5636.2    0.07       0
Bank Sta=4989.5,4993.5
Exp/Cntr=0.3,0.1

Type RM Length L Ch R = 1,25,0,0,0
BEGIN DESCRIPTION:
Chimney Creek 1161 1.0
END DESCRIPTION:
XS GIS Cut Line= 3
      1670143.66      6982503.58      1670030.00      6982587.70
      1669999.27      6983574.52
#Sta/Elev= 30
  4858.6 1664.69  4889.6 1664.06  4895.9 1661.92  4904.3 1661.55  4910.5 1658.05
  4916.3 1658.06  4925.1 1656.50  4950.5 1656.33  4951.0 1655.83  4958.3 1656.33
  4960.6 1657.62  4969.7 1656.87  4989.8 1657.02  4996.0 1658.37  5000.0 1658.37
  5002.7 1657.28  5009.0 1658.61  5060.3 1658.72  5120.4 1662.13  5200.4 1662.95
  5250.4 1661.28  5300.4 1661.56  5450.5 1668.67  5600.6 1673.58  5630.6 1675.38
  5746.0 1679.48  5820.7 1682.85  5880.7 1686.77  5930.7 1690.93  5987.3 1698.04
#Mann=7,-1,0
  4858.6    0.07       0  4916.3   0.035       0  4950.5    0.07       0
  4958.3   0.035       0  4969.7    0.07       0  5009.0   0.035       0
  5746.0    0.07       0
Bank Sta=4950.5,4958.3
Exp/Cntr=0.3,0.1

Chan Stop Cuts=-1