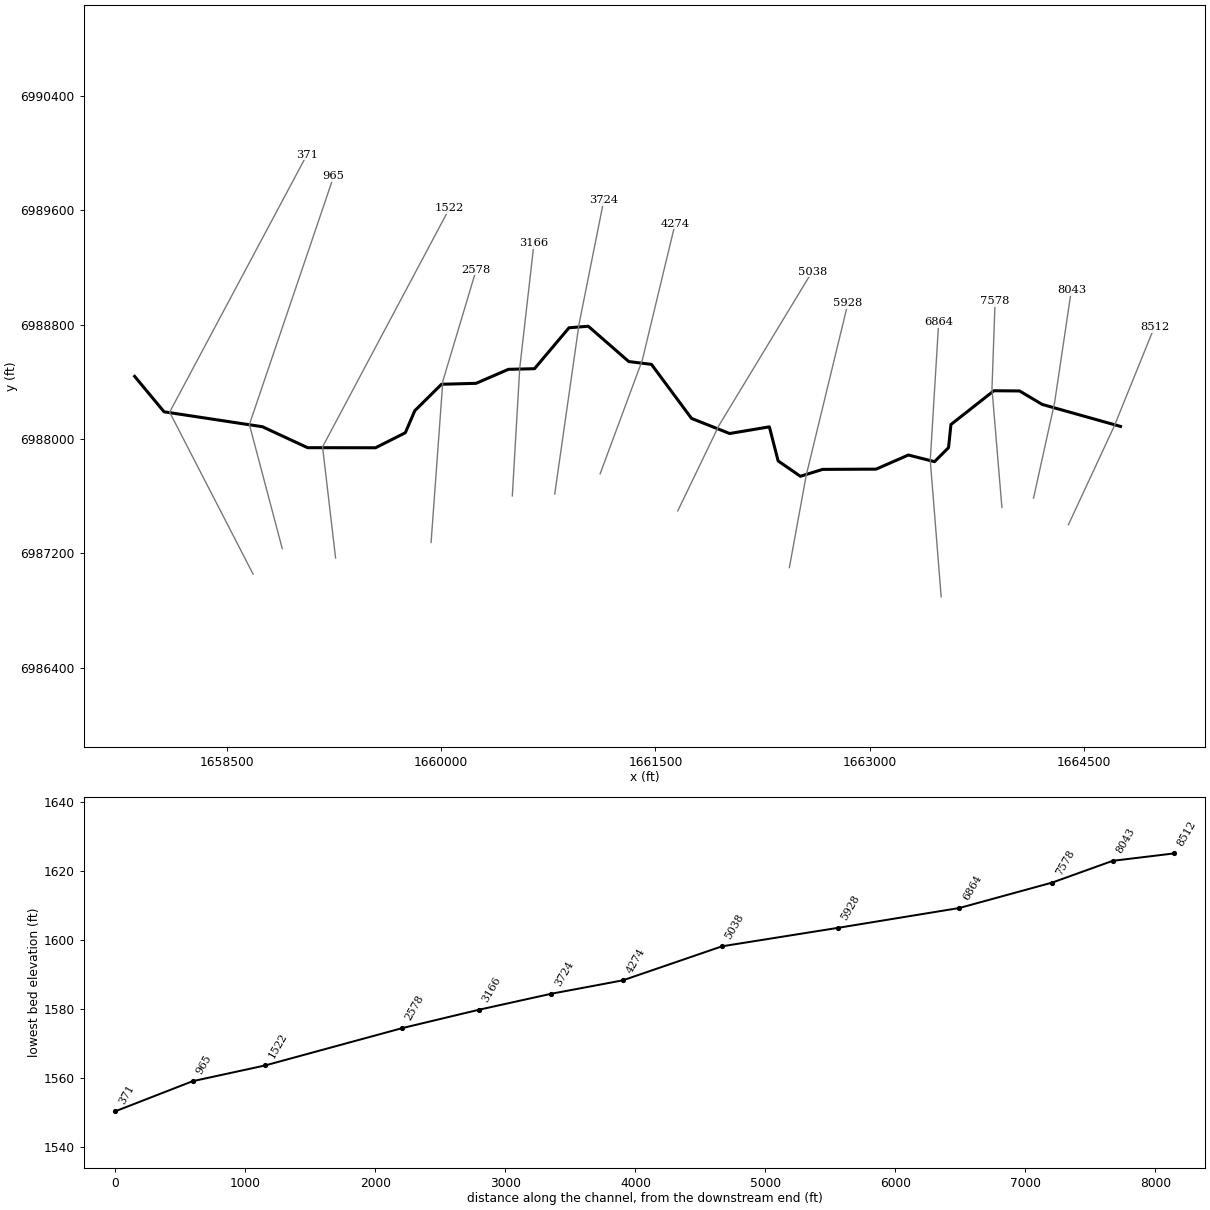
--- Chimney Creek 1162.prj (project) ---

Proj Title=Chimney Creek 1162 Base Level Engineering
Current Plan=p01
Default Exp/Contr=0.3,0.1
English Units
Geom File=g01
Flow File=f01
Plan File=p01
BEGIN DESCRIPTION:
Chimney Creek 1162
END DESCRIPTION:

--- Chimney Creek 1162.p01 (plan) ---

Plan Title=Multiple Run
Short Identifier=Multiple
Geom File=g01
Flow File=f01
Subcritical Flow
K Sum by GR= 0
Std Step Tol= 0.01
Critical Tol= 0.01
Num of Std Step Trials= 20
Max Error Tol= 0.3
Flow Tol Ratio= 0.001
Split Flow NTrial= 30
Split Flow Tol= 0.02
Split Flow Ratio= 0.02
Log Output Level= 0
Friction Slope Method= 1
Unsteady Friction Slope Method= 2
Unsteady Bridges Friction Slope Method= 1
Parabolic Critical Depth
Global Vel Dist=  1 , 1 , 1
Global Log Level= 0
CheckData=True
Encroach Param= -1, 0, 0, 0
BEGIN DESCRIPTION:
Multiple Run
END DESCRIPTION:

--- Chimney Creek 1162.f01 (steady flow) ---

Flow Title=Multiple
Number of Profiles=7
Profile Names=10-year,25-year,50-year,1pct_min,100-year,1pct_plu,500-year
River Rch & RM= Chimney Creek 11,Reach-1,8512
     292     412     513     318     635    1267     987
River Rch & RM= Chimney Creek 11,Reach-1,6864
     385     549     688     430     857    1710    1348
Boundary for River Rch & Prof#=Chimney Creek 11,Reach-1,1
Up Type=0
Dn Type=3
Dn Slope=0.005
Boundary for River Rch & Prof#=Chimney Creek 11,Reach-1,2
Up Type=0
Dn Type=3
Dn Slope=0.005
Boundary for River Rch & Prof#=Chimney Creek 11,Reach-1,3
Up Type=0
Dn Type=3
Dn Slope=0.005
Boundary for River Rch & Prof#=Chimney Creek 11,Reach-1,4
Up Type=0
Dn Type=3
Dn Slope=0.005
Boundary for River Rch & Prof#=Chimney Creek 11,Reach-1,5
Up Type=0
Dn Type=3
Dn Slope=0.005
Boundary for River Rch & Prof#=Chimney Creek 11,Reach-1,6
Up Type=0
Dn Type=3
Dn Slope=0.005
Boundary for River Rch & Prof#=Chimney Creek 11,Reach-1,7
Up Type=0
Dn Type=3
Dn Slope=0.005

--- Chimney Creek 1162.g01 (geometry) ---

Geom Title=Existing Conditions

River Reach=Chimney Creek 11,Reach-1
Reach XY= 30
      1664755.00      6988088.00      1664206.58      6988241.83
      1664049.07      6988335.76      1663868.91      6988337.33
      1663568.37      6988101.32      1663551.46      6987939.46
      1663453.52      6987841.45      1663270.39      6987887.91
      1663044.50      6987789.22      1662670.22      6987787.48
      1662514.68      6987739.24      1662358.82      6987846.56
      1662297.38      6988084.93      1662019.10      6988038.24
      1661752.70      6988143.83      1661472.14      6988521.72
      1661313.44      6988541.41      1661030.11      6988788.32
      1660895.18      6988777.54      1660653.53      6988491.54
      1660470.96      6988487.04      1660244.50      6988389.22
      1660002.55      6988382.54      1659815.77      6988197.68
      1659749.42      6988043.58      1659541.09      6987938.67
      1659065.50      6987939.20      1658749.06      6988085.74
      1658060.86      6988190.07      1657855.00      6988438.00

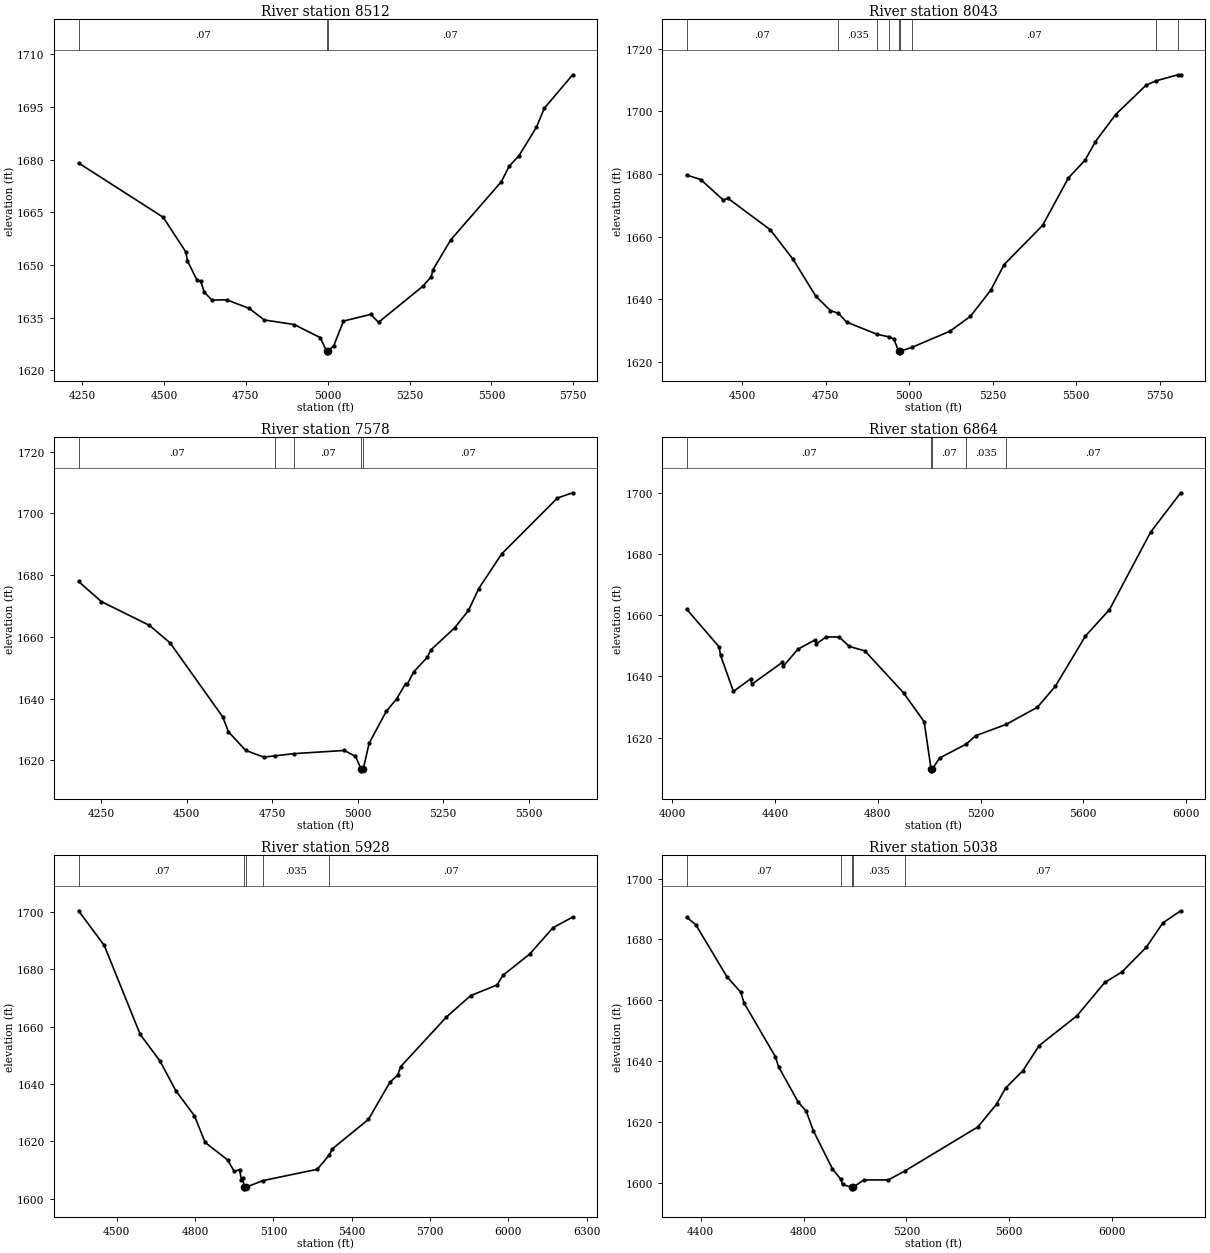
Type RM Length L Ch R = 1,8512,469,469,469
BEGIN DESCRIPTION:
Chimney Creek 1162 18.0
END DESCRIPTION:
XS GIS Cut Line= 3
      1664390.29      6987399.99      1664711.27      6988089.99
      1664992.57      6988783.29
#Sta/Elev= 30
  4239.0 1679.06  4497.5 1663.60  4566.2 1653.79  4571.7 1651.17  4600.8 1645.65
  4611.8 1645.40  4623.0 1642.28  4645.9 1640.01  4691.6 1640.07  4760.3 1637.63
  4806.1 1634.34  4897.6 1633.03  4977.3 1629.30  4996.5 1625.47  4996.7 1624.97
  5000.5 1625.47  5018.6 1627.03  5048.1 1634.02  5131.2 1635.92  5155.3 1633.67
  5291.9 1644.05  5316.0 1646.69  5321.6 1648.67  5375.6 1657.14  5530.3 1673.74
  5554.4 1678.18  5583.9 1681.10  5637.5 1689.25  5661.6 1694.68  5748.2 1704.20
#Mann=3,-1,0
  4239.0    0.07       0  4996.5    0.07       0  5000.5    0.07       0
Bank Sta=4996.5,5000.5
Exp/Cntr=0.3,0.1

Type RM Length L Ch R = 1,8043,465,465,465
BEGIN DESCRIPTION:
Mapping XS 3480894d
END DESCRIPTION:
XS GIS Cut Line= 3
      1664146.35      6987586.57      1664293.93      6988255.02
      1664411.12      6989040.58
#Sta/Elev= 30
  4333.6 1679.67  4376.0 1678.22  4442.9 1671.72  4458.0 1672.18  4584.2 1662.16
  4652.5 1652.70  4720.3 1640.95  4764.0 1636.35  4787.4 1635.51  4812.8 1632.66
  4904.9 1628.72  4939.4 1627.96  4954.1 1627.26  4968.0 1623.34  4968.2 1622.84
  4972.0 1623.34  5008.1 1624.59  5122.1 1629.78  5182.9 1634.49  5243.6 1642.81
  5284.0 1651.05  5399.2 1663.59  5476.1 1678.70  5526.7 1684.49  5557.0 1690.32
  5617.7 1699.00  5708.7 1708.37  5738.4 1709.76  5803.0 1711.67  5812.4 1711.70
#Mann=9,-1,0
  4333.6    0.07       0  4787.4   0.035       0  4904.9    0.07       0
  4939.4   0.035       0  4968.0   0.035       0  4972.0   0.035       0
  5008.1    0.07       0  5738.4   0.035       0  5803.0    0.07       0
Bank Sta=4968,4972
Exp/Cntr=0.3,0.1

Type RM Length L Ch R = 1,7578,714,714,714
BEGIN DESCRIPTION:
Mapping XS 0b6b538f
END DESCRIPTION:
XS GIS Cut Line= 3
      1663925.01      6987521.53      1663855.57      6988350.50
      1663877.27      6988962.44
#Sta/Elev= 30
  4184.3 1677.94  4251.0 1671.42  4391.5 1663.71  4451.7 1658.04  4605.5 1634.07
  4622.3 1629.23  4672.5 1623.19  4725.6 1620.99  4758.4 1621.42  4814.3 1622.13
  4960.8 1623.16  4993.6 1621.26  5010.4 1617.05  5010.7 1616.55  5014.4 1617.05
  5016.2 1617.05  5033.7 1625.55  5083.7 1635.84  5113.7 1639.84  5140.0 1644.83
  5145.0 1644.62  5163.8 1648.61  5203.8 1653.41  5213.8 1655.73  5283.8 1662.95
  5323.9 1668.55  5353.9 1675.64  5421.2 1686.91  5584.0 1705.01  5628.5 1706.70
#Mann=5,-1,0
  4184.3    0.07       0  4758.4   0.035       0  4814.3    0.07       0
  5010.4    0.07       0  5014.4    0.07       0
Bank Sta=5010.4,5014.4
Exp/Cntr=0.3,0.1

Type RM Length L Ch R = 1,6864,936,936,936
BEGIN DESCRIPTION:
Mapping XS e7ed6a05
END DESCRIPTION:
XS GIS Cut Line= 3
      1663500.01      6986896.25      1663423.62      6987851.14
      1663482.54      6988814.70
#Sta/Elev= 30
  4055.9 1661.96  4182.3 1649.66  4188.1 1646.89  4238.2 1635.09  4305.1 1639.19
  4310.2 1637.47  4428.0 1644.54  4433.1 1643.39  4489.0 1648.86  4555.9 1651.89
  4561.0 1650.63  4599.4 1652.88  4649.5 1652.86  4689.7 1649.77  4749.9 1648.33
  4900.3 1634.65  4980.6 1625.22  5007.7 1609.69  5008.0 1609.19  5011.8 1609.69
  5040.7 1613.37  5144.7 1617.93  5181.0 1620.65  5299.7 1624.34  5421.5 1629.94
  5491.6 1636.83  5608.3 1653.16  5702.0 1661.81  5862.3 1687.10  5979.2 1699.91
#Mann=5,-1,0
  4055.9    0.07       0  5007.7    0.07       0  5011.8    0.07       0
  5144.7   0.035       0  5299.7    0.07       0
Bank Sta=5007.7,5011.8
Exp/Cntr=0.3,0.1

Type RM Length L Ch R = 1,5928,890,890,890
BEGIN DESCRIPTION:
Mapping XS 90f5bdb2
END DESCRIPTION:
XS GIS Cut Line= 3
      1662437.51      6987101.16      1662555.57      6987746.97
      1662847.23      6988948.36
#Sta/Elev= 30
  4353.4 1700.34  4451.8 1688.27  4589.4 1657.27  4665.3 1647.97  4726.3 1637.59
  4797.5 1628.86  4838.1 1619.61  4924.0 1613.55  4950.0 1609.48  4970.3 1610.14
  4977.2 1606.49  4982.3 1607.09  4988.4 1603.93  4988.7 1603.43  4992.9 1603.93
  5058.4 1606.28  5268.2 1610.25  5314.5 1615.31  5325.1 1617.34  5463.8 1627.64
  5546.1 1640.58  5575.8 1643.01  5587.2 1646.01  5762.2 1663.27  5854.8 1670.74
  5956.9 1674.50  5978.3 1677.79  6081.2 1685.23  6170.9 1694.45  6246.2 1698.14
#Mann=5,-1,0
  4353.4    0.07       0  4988.4    0.07       0  4992.9    0.07       0
  5058.4   0.035       0  5314.5    0.07       0
Bank Sta=4988.4,4992.9
Exp/Cntr=0.3,0.1

Type RM Length L Ch R = 1,5038,764,764,764
BEGIN DESCRIPTION:
Mapping XS e3a8ae67
END DESCRIPTION:
XS GIS Cut Line= 3
      1661656.25      6987496.96      1661944.45      6988094.20
      1662597.23      6989170.58
#Sta/Elev= 30
  4344.7 1687.29  4380.5 1684.85  4501.3 1667.80  4555.8 1662.62  4567.9 1659.18
  4690.1 1641.48  4702.6 1638.18  4778.9 1626.58  4810.1 1623.59  4838.2 1617.10
  4912.1 1604.65  4944.4 1601.27  4951.3 1599.53  4987.6 1598.60  4987.9 1598.10
  4992.2 1598.60  5033.8 1601.02  5128.8 1601.02  5193.6 1603.95  5477.8 1618.44
  5550.3 1625.91  5585.4 1631.18  5652.3 1636.85  5716.3 1645.15  5863.6 1654.96
  5971.3 1665.89  6038.1 1669.30  6133.1 1677.46  6197.1 1685.41  6266.7 1689.41
#Mann=5,-1,0
  4344.7    0.07       0  4944.4   0.035       0  4987.6   0.035       0
  4992.2   0.035       0  5193.6    0.07       0
Bank Sta=4987.6,4992.2
Exp/Cntr=0.3,0.1

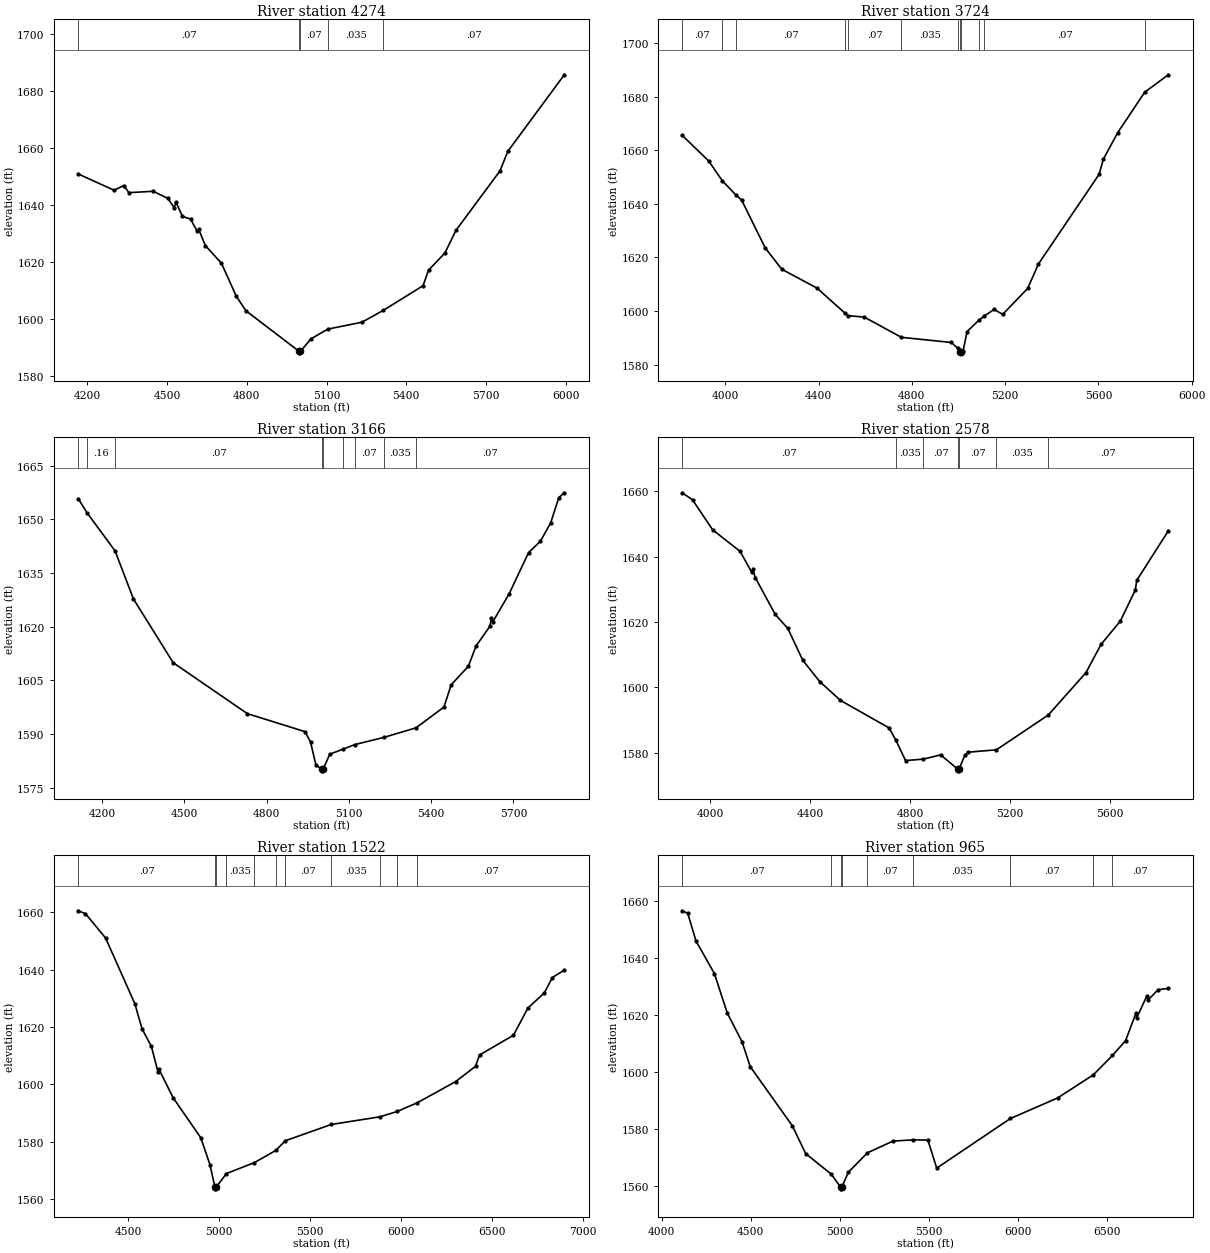
Type RM Length L Ch R = 1,4274,550,550,550
BEGIN DESCRIPTION:
Mapping XS f759eec5
END DESCRIPTION:
XS GIS Cut Line= 3
      1661112.87      6987756.55      1661408.00      6988550.79
      1661637.71      6989504.31
#Sta/Elev= 30
  4166.0 1650.87  4301.1 1645.17  4338.2 1646.81  4356.5 1644.32  4447.6 1644.80
  4502.9 1642.35  4528.0 1638.95  4533.3 1641.05  4558.3 1636.01  4588.7 1635.07
  4613.7 1630.78  4619.0 1631.59  4644.1 1625.81  4704.8 1619.62  4760.1 1608.14
  4797.0 1602.95  4997.3 1588.74  4997.6 1588.24  5002.0 1588.74  5041.3 1593.14
  5104.9 1596.55  5233.5 1598.97  5313.3 1603.09  5463.0 1611.75  5483.6 1617.19
  5545.3 1623.21  5586.5 1631.11  5751.9 1651.89  5781.9 1658.80  5994.1 1685.59
#Mann=5,-1,0
  4166.0    0.07       0  4997.3    0.07       0  5002.0    0.07       0
  5104.9   0.035       0  5313.3    0.07       0
Bank Sta=4997.3,5002
Exp/Cntr=0.3,0.1

Type RM Length L Ch R = 1,3724,558,558,558
BEGIN DESCRIPTION:
Mapping XS f8583249
END DESCRIPTION:
XS GIS Cut Line= 3
      1660795.18      6987615.46      1660965.32      6988802.97
      1661138.94      6989671.04
#Sta/Elev= 30
  3815.0 1665.60  3928.7 1656.02  3987.0 1648.64  4046.5 1643.22  4070.1 1641.39
  4171.1 1623.55  4241.9 1615.60  4393.4 1608.53  4512.8 1599.20  4526.3 1598.25
  4595.4 1597.73  4755.3 1590.15  4969.2 1588.23  4997.4 1586.01  5007.2 1584.86
  5007.5 1584.36  5012.0 1584.86  5019.8 1585.08  5036.8 1592.30  5087.1 1596.53
  5110.3 1598.08  5152.3 1600.56  5189.7 1598.73  5296.8 1608.44  5342.7 1617.53
  5602.8 1651.02  5621.4 1656.73  5682.6 1666.56  5798.7 1681.72  5899.9 1688.23
#Mann=12,-1,0
  3815.0    0.07       0  3987.0    0.16       0  4046.5    0.07       0
  4512.8   0.035       0  4526.3    0.07       0  4755.3   0.035       0
  4997.4    0.07       0  5007.2    0.07       0  5012.0    0.07       0
  5087.1   0.035       0  5110.3    0.07       0  5798.7   0.035       0
Bank Sta=5007.2,5012
Exp/Cntr=0.3,0.1

Type RM Length L Ch R = 1,3166,588,588,588
BEGIN DESCRIPTION:
Mapping XS 9d19eac2
END DESCRIPTION:
XS GIS Cut Line= 3
      1660498.27      6987601.99      1660550.36      6988496.11
      1660650.09      6989367.68
#Sta/Elev= 30
  4112.4 1655.81  4144.4 1651.87  4247.0 1641.18  4313.9 1627.77  4459.0 1609.93
  4729.5 1595.70  4939.8 1590.67  4959.8 1587.77  4979.9 1581.23  5001.0 1580.22
  5001.3 1579.72  5005.9 1580.22  5030.1 1584.38  5076.5 1585.72  5121.6 1587.06
  5227.2 1589.06  5344.8 1591.75  5446.2 1597.54  5472.9 1603.77  5535.5 1608.95
  5563.5 1614.60  5613.9 1620.12  5619.8 1622.51  5624.8 1621.39  5684.3 1629.21
  5754.8 1640.68  5798.3 1643.89  5835.3 1648.95  5865.5 1656.09  5885.3 1657.42
#Mann=9,-1,0
  4112.4    0.07       0  4144.4    0.16       0  4247.0    0.07       0
  5001.0    0.07       0  5005.9    0.07       0  5076.5   0.035       0
  5121.6    0.07       0  5227.2   0.035       0  5344.8    0.07       0
Bank Sta=5001,5005.9
Exp/Cntr=0.3,0.1

Type RM Length L Ch R = 1,2578,1056,1056,1056
BEGIN DESCRIPTION:
Mapping XS 565562a0
END DESCRIPTION:
XS GIS Cut Line= 3
      1659929.70      6987276.47      1660012.16      6988404.96
      1660246.07      6989184.64
#Sta/Elev= 30
  3887.6 1659.60  3929.2 1657.43  4009.4 1648.26  4119.7 1641.63  4165.5 1635.28
  4170.5 1636.13  4179.9 1633.64  4260.1 1622.33  4310.2 1618.05  4370.4 1608.26
  4438.1 1601.77  4520.8 1596.01  4715.7 1587.56  4743.1 1583.75  4781.5 1577.57
  4852.5 1578.00  4921.9 1579.32  4990.7 1574.92  4991.1 1574.42  4995.7 1574.92
  5018.1 1579.12  5032.7 1580.14  5145.0 1580.86  5352.5 1591.51  5503.3 1604.48
  5564.2 1613.19  5640.7 1620.25  5700.9 1629.79  5706.8 1632.77  5833.1 1647.94
#Mann=7,-1,0
  3887.6    0.07       0  4743.1   0.035       0  4852.5    0.07       0
  4990.7    0.07       0  4995.7    0.07       0  5145.0   0.035       0
  5352.5    0.07       0
Bank Sta=4990.7,4995.7
Exp/Cntr=0.3,0.1

Type RM Length L Ch R = 1,1522,557,557,557
BEGIN DESCRIPTION:
Mapping XS daf45d1e
END DESCRIPTION:
XS GIS Cut Line= 3
      1659261.29      6987168.03      1659170.15      6987944.89
      1660059.14      6989614.47
#Sta/Elev= 30
  4224.8 1660.49  4265.0 1659.49  4375.8 1650.99  4536.9 1628.05  4575.7 1619.43
  4627.5 1613.23  4663.9 1604.31  4668.9 1605.28  4747.1 1595.34  4899.4 1581.38
  4949.7 1572.00  4977.3 1564.10  4977.7 1563.60  4982.5 1564.10  5040.1 1568.92
  5194.0 1572.74  5312.2 1577.00  5364.3 1580.36  5616.5 1586.02  5885.9 1588.72
  5980.0 1590.57  6090.6 1593.62  6300.5 1600.94  6410.3 1606.31  6432.3 1610.24
  6618.7 1617.11  6698.6 1626.63  6788.7 1631.86  6832.7 1637.22  6898.5 1639.81
#Mann=11,-1,0
  4224.8    0.07       0  4977.3    0.07       0  4982.5    0.07       0
  5040.1   0.035       0  5194.0    0.07       0  5312.2   0.035       0
  5364.3    0.07       0  5616.5   0.035       0  5885.9    0.07       0
  5980.0   0.035       0  6090.6    0.07       0
Bank Sta=4977.3,4982.5
Exp/Cntr=0.3,0.1

Type RM Length L Ch R = 1,965,594,594,594
BEGIN DESCRIPTION:
Mapping XS 618389ec
END DESCRIPTION:
XS GIS Cut Line= 3
      1658888.03      6987233.07      1658658.00      6988101.14
      1659248.26      6989837.21
#Sta/Elev= 30
  4115.5 1656.49  4146.7 1655.60  4193.0 1645.92  4296.5 1634.48  4368.9 1620.65
  4451.6 1610.60  4498.2 1601.84  4734.3 1581.16  4809.5 1571.39  4952.6 1564.22
  5007.0 1559.55  5007.4 1559.05  5012.2 1559.55  5049.0 1564.85  5156.3 1571.67
  5300.0 1575.78  5414.1 1576.22  5496.1 1576.13  5545.7 1566.31  5959.9 1583.70
  6224.9 1590.89  6425.3 1598.98  6533.4 1605.79  6607.2 1611.00  6664.7 1620.52
  6670.0 1619.01  6727.5 1626.77  6732.7 1625.18  6790.2 1628.85  6847.2 1629.28
#Mann=9,-1,0
  4115.5    0.07       0  4952.6   0.035       0  5007.0   0.035       0
  5012.2   0.035       0  5156.3    0.07       0  5414.1   0.035       0
  5959.9    0.07       0  6425.3   0.035       0  6533.4    0.07       0
Bank Sta=5007,5012.2
Exp/Cntr=0.3,0.1

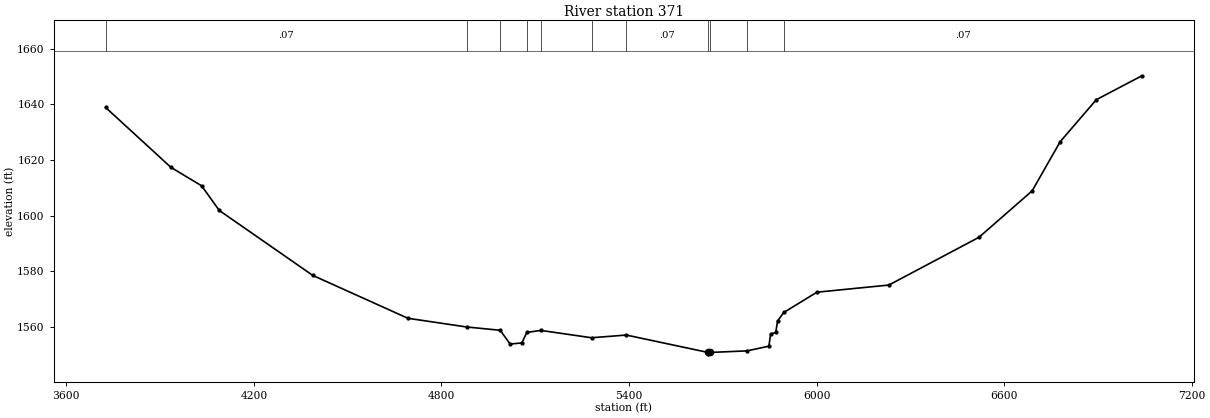
Type RM Length L Ch R = 1,371,0,0,0
BEGIN DESCRIPTION:
Chimney Creek 1162 1.0
END DESCRIPTION:
XS GIS Cut Line= 3
      1658684.06      6987055.10      1658099.83      6988187.58
      1659060.82      6989987.62
#Sta/Elev= 30
  3725.7 1638.84  3934.0 1617.38  4032.8 1610.69  4089.1 1601.86  4388.1 1578.53
  4692.6 1563.12  4880.5 1560.00  4987.9 1558.81  5019.5 1553.87  5057.2 1554.27
  5072.7 1558.02  5117.4 1558.77  5280.0 1556.13  5391.3 1557.10  5652.8 1550.85
  5653.2 1550.35  5658.0 1550.85  5777.1 1551.41  5847.3 1553.10  5853.0 1557.48
  5869.3 1558.02  5875.0 1562.16  5895.1 1565.22  6001.0 1572.49  6231.2 1575.06
  6519.5 1592.22  6689.5 1608.89  6779.2 1626.55  6894.7 1641.63  7040.5 1650.23
#Mann=11,-1,0
  3725.7    0.07       0  4880.5   0.035       0  4987.9    0.16       0
  5072.7   0.035       0  5117.4    0.07       0  5280.0   0.035       0
  5391.3    0.07       0  5652.8    0.07       0  5658.0    0.07       0
  5777.1    0.16       0  5895.1    0.07       0
Bank Sta=5652.8,5658
Exp/Cntr=0.3,0.1

Chan Stop Cuts=-1