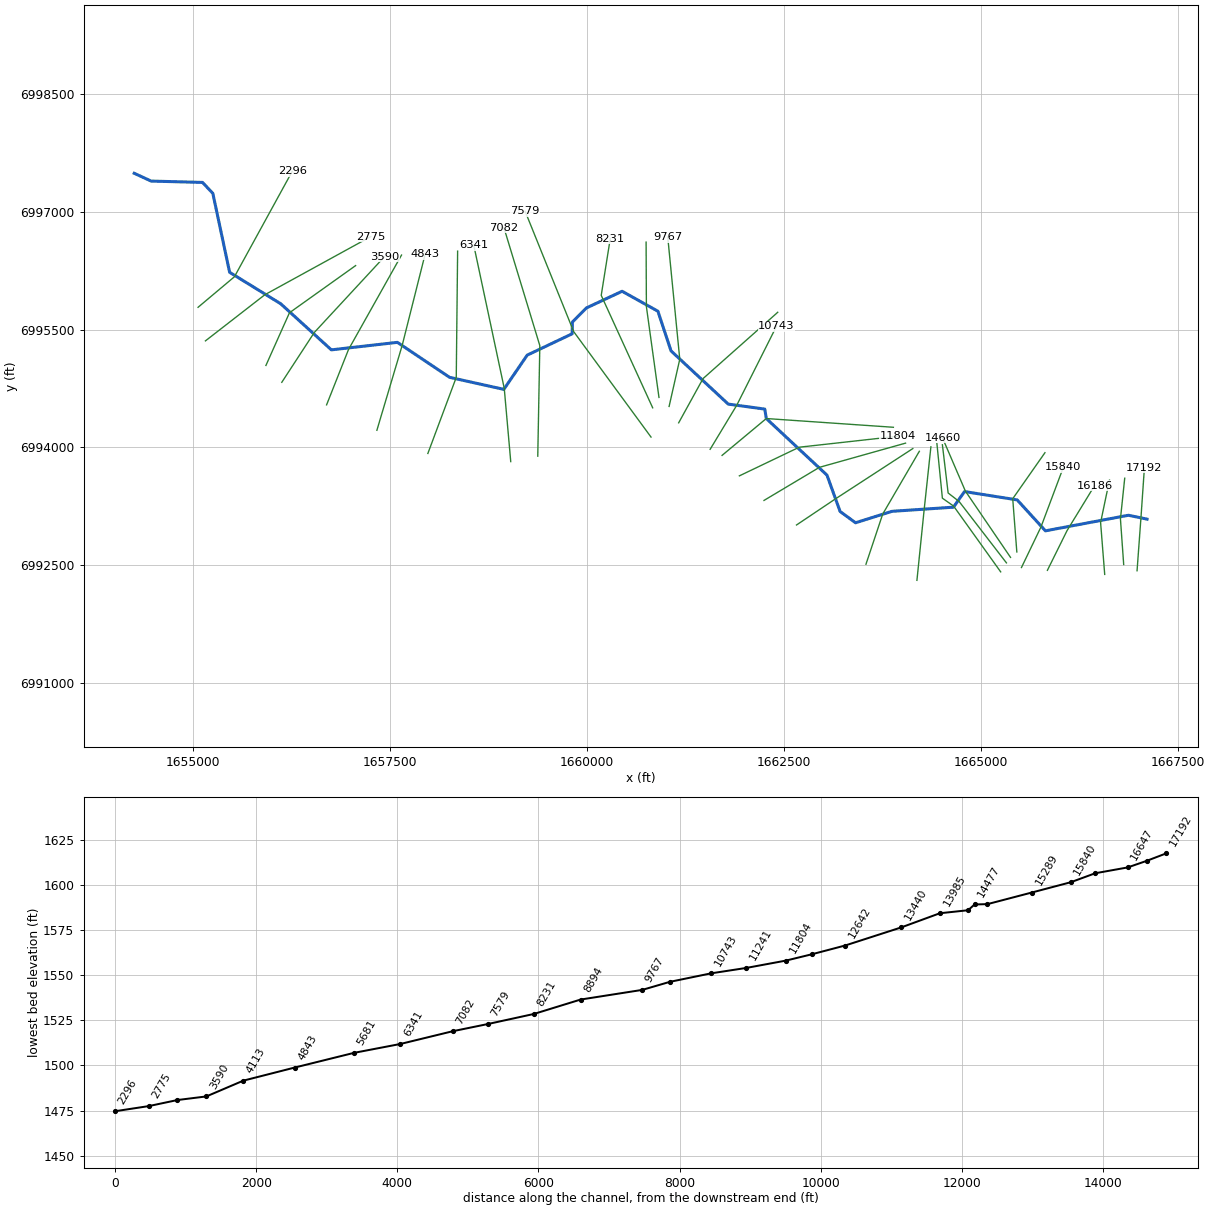
--- Chimney Creek 1163.prj (project) ---

Proj Title=Chimney Creek 1163 Base Level Engineering
Current Plan=p01
Default Exp/Contr=0.3,0.1
English Units
Geom File=g01
Flow File=f01
Plan File=p01
BEGIN DESCRIPTION:
Chimney Creek 1163
END DESCRIPTION:

--- Chimney Creek 1163.p01 (plan) ---

Plan Title=Multiple Run
Short Identifier=Multiple
Geom File=g01
Flow File=f01
Subcritical Flow
K Sum by GR= 0
Std Step Tol= 0.01
Critical Tol= 0.01
Num of Std Step Trials= 20
Max Error Tol= 0.3
Flow Tol Ratio= 0.001
Split Flow NTrial= 30
Split Flow Tol= 0.02
Split Flow Ratio= 0.02
Log Output Level= 0
Friction Slope Method= 1
Unsteady Friction Slope Method= 2
Unsteady Bridges Friction Slope Method= 1
Parabolic Critical Depth
Global Vel Dist=  1 , 1 , 1
Global Log Level= 0
CheckData=True
Encroach Param= -1, 0, 0, 0
BEGIN DESCRIPTION:
Multiple Run
END DESCRIPTION:

--- Chimney Creek 1163.f01 (steady flow) ---

Flow Title=Multiple
Number of Profiles=7
Profile Names=10-year,25-year,50-year,1pct_min,100-year,1pct_plu,500-year
River Rch & RM= Chimney Creek 11,Reach-1,17192
     317     448     559     348     694    1384    1083
River Rch & RM= Chimney Creek 11,Reach-1,15840
     399     573     723     454     906    1807    1440
River Rch & RM= Chimney Creek 11,Reach-1,10743
     722    1068    1372     877    1750    3492    2885
River Rch & RM= Chimney Creek 11,Reach-1,6341
     895    1335    1726    1109    2213    4416    3688
River Rch & RM= Chimney Creek 11,Reach-1,2296
     958    1433    1856    1195    2383    4755    3984
Boundary for River Rch & Prof#=Chimney Creek 11,Reach-1,1
Up Type=0
Dn Type=3
Dn Slope=0.005
Boundary for River Rch & Prof#=Chimney Creek 11,Reach-1,2
Up Type=0
Dn Type=3
Dn Slope=0.005
Boundary for River Rch & Prof#=Chimney Creek 11,Reach-1,3
Up Type=0
Dn Type=3
Dn Slope=0.005
Boundary for River Rch & Prof#=Chimney Creek 11,Reach-1,4
Up Type=0
Dn Type=3
Dn Slope=0.005
Boundary for River Rch & Prof#=Chimney Creek 11,Reach-1,5
Up Type=0
Dn Type=3
Dn Slope=0.005
Boundary for River Rch & Prof#=Chimney Creek 11,Reach-1,6
Up Type=0
Dn Type=3
Dn Slope=0.005
Boundary for River Rch & Prof#=Chimney Creek 11,Reach-1,7
Up Type=0
Dn Type=3
Dn Slope=0.005

--- Chimney Creek 1163.g01 (geometry) ---

Geom Title=Existing Conditions

River Reach=Chimney Creek 11,Reach-1
Reach XY= 30
      1667105.00      6993088.00      1666868.91      6993137.33
      1665815.50      6992939.20      1665457.71      6993332.60
      1664789.32      6993438.69      1664649.16      6993240.05
      1663868.92      6993187.32      1663406.58      6993041.67
      1663210.83      6993185.69      1663044.48      6993647.79
      1662274.62      6994367.84      1662255.00      6994488.00
      1661791.67      6994551.39      1661065.76      6995228.32
      1660899.56      6995732.75      1660445.41      6995986.81
      1659991.79      6995774.37      1659814.15      6995594.73
      1659811.55      6995445.75      1659241.44      6995174.51
      1658944.57      6994739.04      1658256.58      6994891.83
      1657594.49      6995336.80      1656756.46      6995241.54
      1656114.68      6995827.24      1655465.76      6996228.32
      1655252.93      6997232.14      1655121.75      6997371.54
      1654470.22      6997388.52      1654255.00      6997488.00

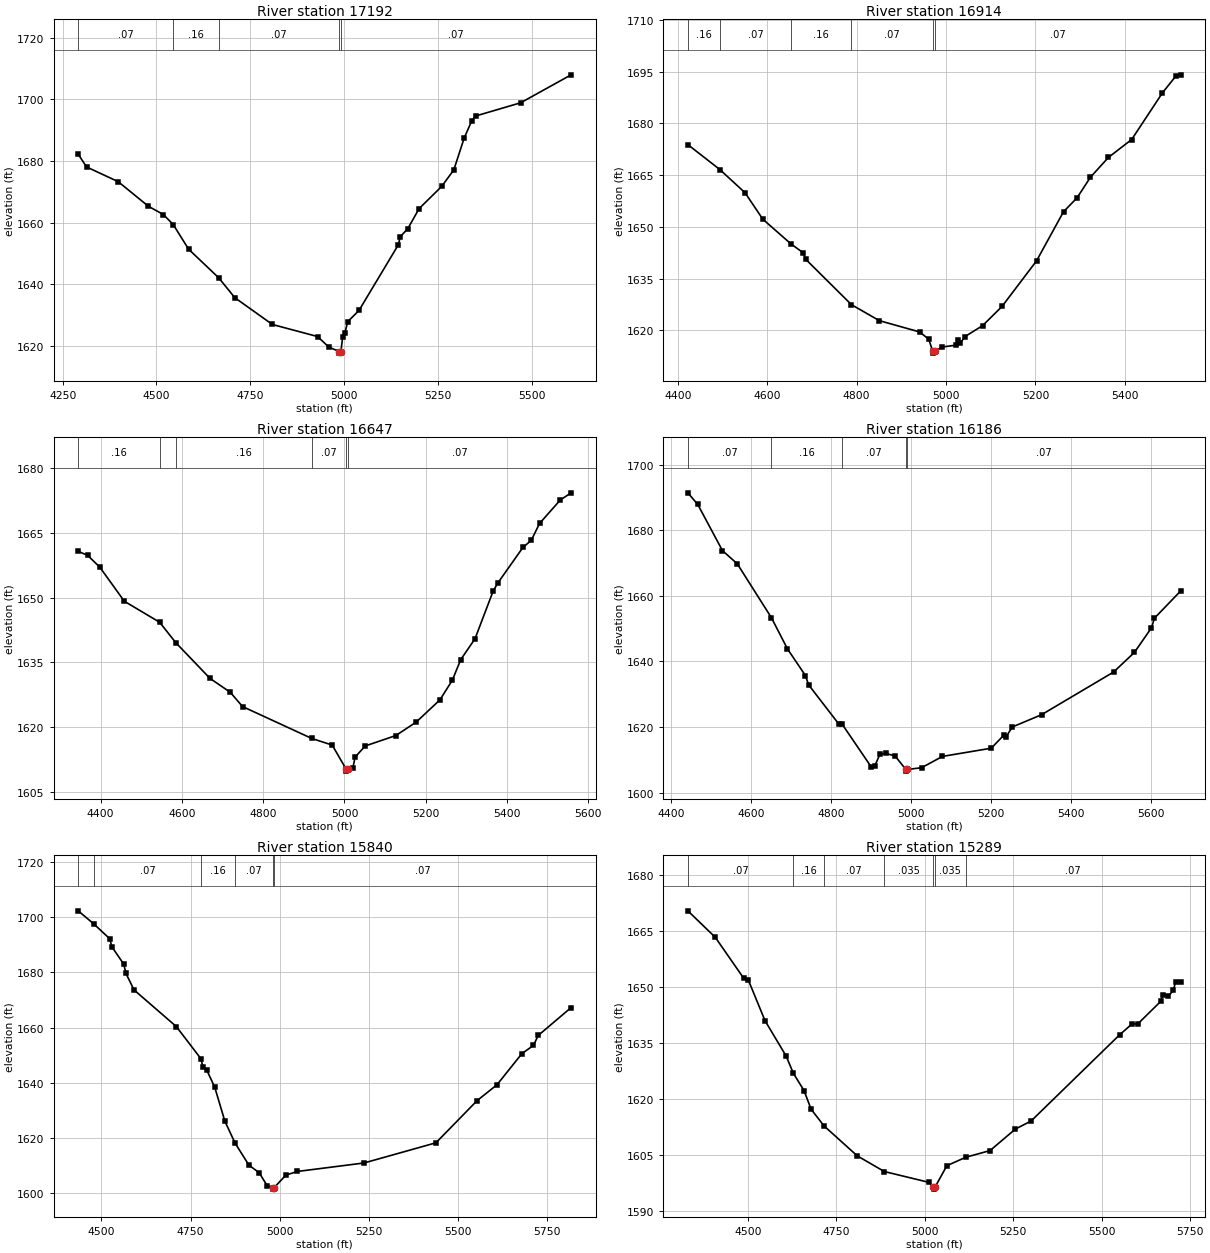
Type RM Length L Ch R = 1,17192,278,278,278
BEGIN DESCRIPTION:
Chimney Creek 1163 37.0
END DESCRIPTION:
XS GIS Cut Line= 3
      1666978.32      6992431.54      1667030.10      6993138.24
      1667071.64      6993742.32
#Sta/Elev= 30
  4291.4 1682.22  4313.7 1678.07  4398.1 1673.28  4478.4 1665.30  4518.5 1662.59
  4544.9 1659.32  4585.9 1651.31  4666.0 1642.03  4709.0 1635.55  4809.2 1626.85
  4929.6 1622.93  4959.6 1619.50  4987.7 1618.04  4988.0 1617.54  4991.7 1618.04
  4996.7 1622.93  5002.4 1624.09  5009.8 1627.76  5039.9 1631.40  5144.7 1652.72
  5150.1 1655.40  5170.2 1658.02  5200.2 1664.52  5260.4 1671.74  5292.8 1677.12
  5320.5 1687.51  5340.6 1693.06  5350.6 1694.62  5470.9 1698.93  5605.5 1708.02
#Mann=5,-1,0
  4291.4    0.07       0  4544.9    0.16       0  4666.0    0.07       0
  4987.7    0.07       0  4991.7    0.07       0
Bank Sta=4987.7,4991.7
Exp/Cntr=0.3,0.1

Type RM Length L Ch R = 1,16914,267,267,267
BEGIN DESCRIPTION:
Mapping XS 0e2771b8
END DESCRIPTION:
XS GIS Cut Line= 3
      1666808.76      6992510.71      1666767.53      6993090.18
      1666821.78      6993608.81
#Sta/Elev= 30
  4422.6 1673.83  4494.1 1666.61  4550.6 1659.87  4590.3 1652.20  4653.4 1645.03
  4680.5 1642.48  4686.2 1640.59  4788.5 1627.43  4851.0 1622.79  4941.2 1619.51
  4961.3 1617.41  4970.5 1613.88  4970.7 1613.38  4974.5 1613.88  4991.3 1615.15
  5021.5 1615.67  5026.9 1617.23  5031.9 1616.19  5041.6 1618.11  5081.8 1621.35
  5125.2 1626.91  5202.4 1640.12  5262.8 1654.38  5292.9 1658.38  5323.1 1664.39
  5363.3 1670.12  5415.2 1675.31  5484.0 1688.83  5514.1 1693.72  5525.0 1694.06
#Mann=6,-1,0
  4422.6    0.16       0  4494.1    0.07       0  4653.4    0.16       0
  4788.5    0.07       0  4970.5    0.07       0  4974.5    0.07       0
Bank Sta=4970.5,4974.5
Exp/Cntr=0.3,0.1

Type RM Length L Ch R = 1,16647,461,461,461
BEGIN DESCRIPTION:
Mapping XS ff7926d5
END DESCRIPTION:
XS GIS Cut Line= 3
      1666567.87      6992384.89      1666515.79      6993044.60
      1666628.44      6993584.00
#Sta/Elev= 30
  4344.8 1660.73  4368.0 1659.81  4398.1 1657.05  4458.3 1649.16  4545.2 1644.29
  4584.7 1639.58  4668.9 1631.29  4719.1 1628.04  4749.2 1624.74  4919.6 1617.34
  4969.8 1615.81  5003.8 1610.27  5004.0 1609.77  5007.8 1610.27  5020.3 1610.41
  5026.3 1613.04  5050.9 1615.60  5126.3 1618.02  5176.3 1621.13  5234.8 1626.29
  5265.4 1630.86  5285.9 1635.61  5321.1 1640.46  5366.0 1651.58  5377.8 1653.46
  5439.1 1661.65  5459.5 1663.27  5480.0 1667.21  5531.0 1672.64  5557.6 1674.30
#Mann=6,-1,0
  4344.8    0.16       0  4545.2    0.07       0  4584.7    0.16       0
  4919.6    0.07       0  5003.8    0.07       0  5007.8    0.07       0
Bank Sta=5003.8,5007.8
Exp/Cntr=0.3,0.1

Type RM Length L Ch R = 1,16186,346,346,346
BEGIN DESCRIPTION:
Mapping XS c830ecb6
END DESCRIPTION:
XS GIS Cut Line= 3
      1665840.89      6992436.99      1666090.44      6992942.61
      1666439.06      6993514.24
#Sta/Elev= 30
  4441.6 1691.40  4466.4 1687.86  4528.2 1673.78  4565.4 1669.74  4650.8 1653.30
  4690.9 1643.80  4735.8 1635.69  4743.8 1632.84  4820.0 1620.79  4828.0 1620.80
  4899.9 1607.91  4909.8 1608.23  4922.3 1611.72  4937.8 1611.93  4960.3 1611.12
  4987.2 1607.03  4987.4 1606.53  4991.2 1607.03  5026.6 1607.58  5078.8 1611.02
  5200.8 1613.52  5231.8 1617.44  5237.6 1616.88  5253.1 1619.97  5326.6 1623.73
  5506.8 1636.74  5559.0 1642.73  5601.6 1650.22  5609.1 1653.17  5675.0 1661.51
#Mann=5,-1,0
  4441.6    0.07       0  4650.8    0.16       0  4828.0    0.07       0
  4987.2    0.07       0  4991.2    0.07       0
Bank Sta=4987.2,4991.2
Exp/Cntr=0.3,0.1

Type RM Length L Ch R = 1,15840,551,551,551
BEGIN DESCRIPTION:
Mapping XS a437ffbf
END DESCRIPTION:
XS GIS Cut Line= 3
      1665512.03      6992472.70      1665758.56      6992986.59
      1666043.27      6993746.97
#Sta/Elev= 30
  4434.9 1702.29  4478.8 1697.53  4523.3 1692.19  4529.5 1689.23  4562.8 1682.96
  4568.6 1679.70  4591.3 1673.68  4710.1 1660.39  4779.2 1648.72  4784.6 1645.68
  4795.1 1644.71  4817.8 1638.41  4846.0 1626.18  4874.7 1618.22  4913.9 1610.18
  4942.1 1607.53  4964.8 1602.77  4979.7 1602.06  4980.0 1601.56  4984.0 1602.06
  5017.0 1606.62  5049.1 1607.95  5236.5 1611.03  5437.8 1618.33  5553.5 1633.63
  5608.8 1639.31  5679.1 1650.65  5711.1 1653.55  5724.5 1657.17  5816.8 1667.28
#Mann=6,-1,0
  4434.9    0.16       0  4478.8    0.07       0  4779.2    0.16       0
  4874.7    0.07       0  4979.7    0.07       0  4984.0    0.07       0
Bank Sta=4979.7,4984
Exp/Cntr=0.3,0.1

Type RM Length L Ch R = 1,15289,629,629,629
BEGIN DESCRIPTION:
Mapping XS 8fbe20f9
END DESCRIPTION:
XS GIS Cut Line= 3
      1665453.00      6992670.60      1665400.92      6993347.70
      1665809.79      6993933.28
#Sta/Elev= 30
  4330.6 1670.29  4408.2 1663.21  4488.5 1652.26  4501.8 1651.74  4548.6 1640.95
  4608.8 1631.39  4628.7 1626.88  4659.0 1622.23  4679.0 1617.24  4715.5 1612.78
  4809.4 1604.77  4885.9 1600.58  5012.9 1597.66  5024.8 1596.37  5025.1 1595.87
  5029.1 1596.37  5062.7 1602.13  5116.2 1604.39  5184.8 1606.18  5256.4 1611.93
  5300.9 1614.09  5551.2 1637.15  5587.0 1640.11  5601.8 1639.99  5667.2 1646.07
  5673.3 1647.82  5688.2 1647.44  5703.0 1648.99  5709.1 1651.30  5723.9 1651.26
#Mann=7,-1,0
  4330.6    0.07       0  4628.7    0.16       0  4715.5    0.07       0
  4885.9   0.035       0  5024.8   0.035       0  5029.1   0.035       0
  5116.2    0.07       0
Bank Sta=5024.8,5029.1
Exp/Cntr=0.3,0.1

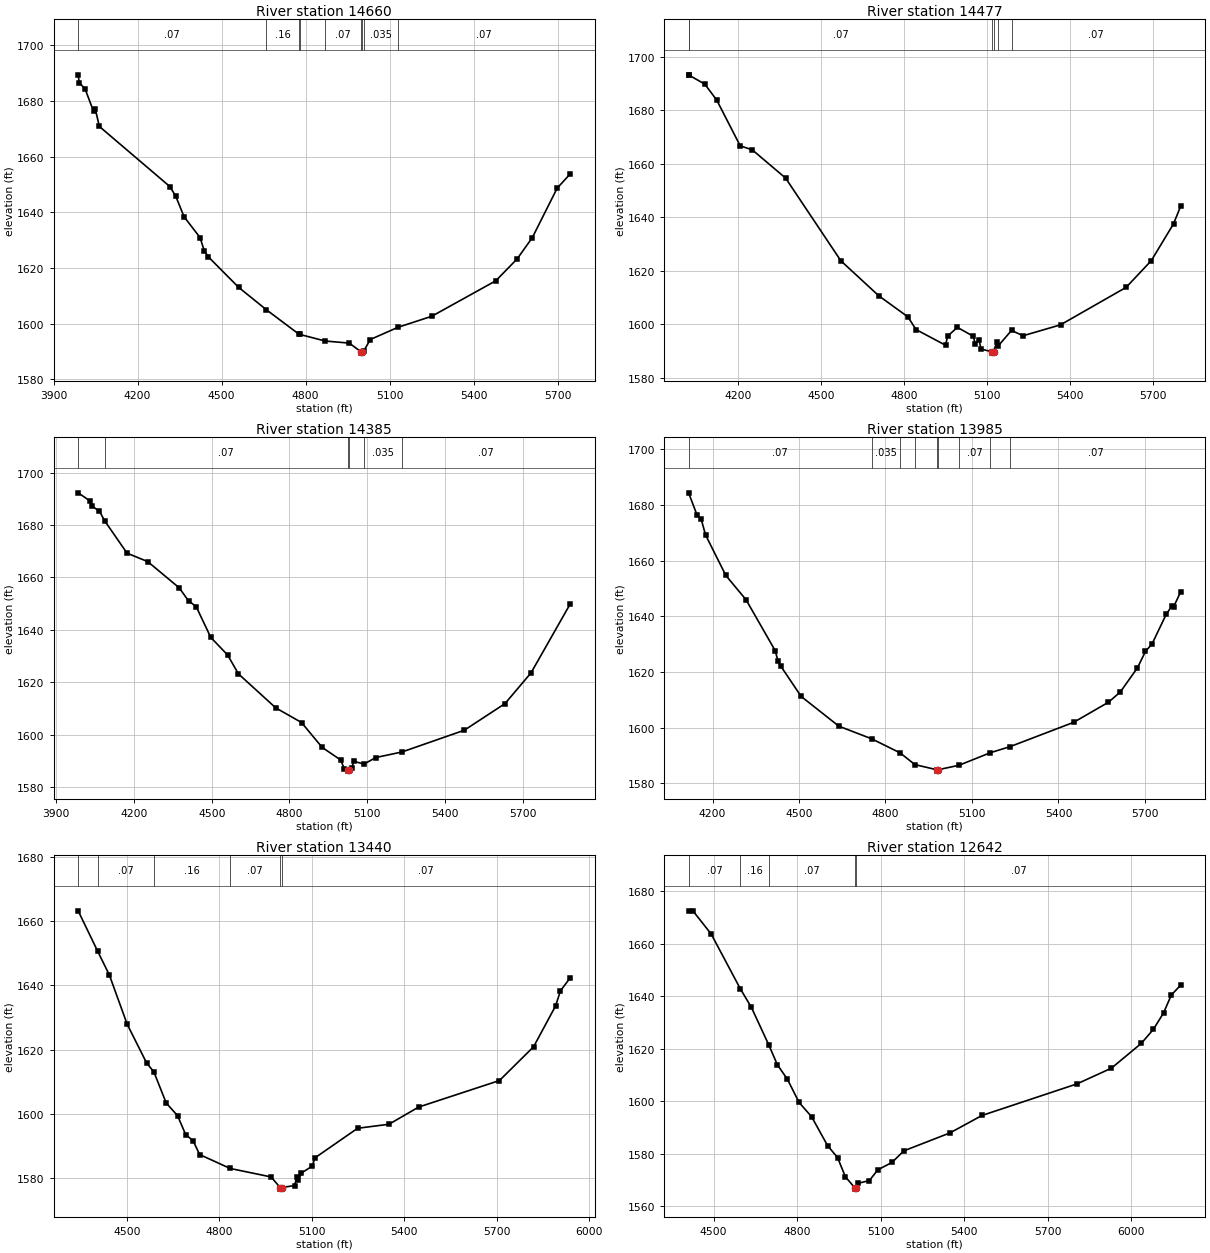
Type RM Length L Ch R = 1,14660,183,183,183
BEGIN DESCRIPTION:
Mapping XS e8b278c7
END DESCRIPTION:
XS GIS Cut Line= 3
      1665373.17      6992601.13      1664800.22      6993444.92
      1664509.80      6994122.59
#Sta/Elev= 30
  3987.7 1689.44  3991.6 1686.62  4012.6 1684.35  4042.5 1676.35  4048.6 1677.24
  4063.5 1670.88  4315.0 1649.30  4336.0 1645.85  4365.9 1638.42  4422.8 1630.98
  4437.8 1626.25  4452.7 1624.01  4560.5 1613.08  4659.5 1605.04  4775.7 1596.25
  4779.5 1596.14  4869.6 1593.78  4955.8 1593.03  4997.1 1589.93  4997.4 1589.43
  5001.5 1589.93  5008.0 1590.27  5030.4 1594.31  5129.5 1598.71  5250.3 1602.68
  5478.8 1615.43  5555.0 1623.30  5609.4 1630.98  5697.7 1648.69  5744.9 1653.88
#Mann=9,-1,0
  3987.7    0.07       0  4659.5    0.16       0  4775.7    0.07       0
  4779.5   0.035       0  4869.6    0.07       0  4997.1    0.07       0
  5001.5    0.07       0  5008.0   0.035       0  5129.5    0.07       0
Bank Sta=4997.1,5001.5
Exp/Cntr=0.3,0.1

Type RM Length L Ch R = 1,14477,92,92,92
BEGIN DESCRIPTION:
Mapping XS 5e95a145
END DESCRIPTION:
XS GIS Cut Line= 4
      1665321.07      6992531.71      1664720.36      6993312.98
      1664581.47      6993420.61      1664508.69      6994034.09
#Sta/Elev= 30
  4021.9 1693.29  4023.0 1693.19  4080.3 1689.82  4123.3 1683.89  4208.4 1666.74
  4252.0 1665.24  4372.5 1654.68  4572.2 1623.76  4708.7 1610.72  4814.7 1602.77
  4843.7 1598.06  4950.7 1592.17  4957.9 1595.56  4993.2 1598.87  5051.1 1595.51
  5057.4 1592.68  5071.9 1594.31  5078.3 1590.74  5119.5 1589.73  5119.8 1589.23
  5123.9 1589.73  5136.2 1593.51  5141.6 1592.01  5189.0 1597.71  5230.8 1595.73
  5366.1 1599.81  5603.4 1613.83  5694.1 1623.80  5774.6 1637.57  5800.9 1644.31
#Mann=6,-1,0
  4021.9    0.16       0  4023.0    0.07       0  5119.5    0.07       0
  5123.9    0.07       0  5141.6   0.035       0  5189.0    0.07       0
Bank Sta=5119.5,5123.9
Exp/Cntr=0.3,0.1

Type RM Length L Ch R = 1,14385,400,400,400
BEGIN DESCRIPTION:
Mapping XS 6eb52082
END DESCRIPTION:
XS GIS Cut Line= 4
      1665248.16      6992417.12      1664650.92      6993253.95
      1664508.56      6993354.64      1664439.11      6994049.11
#Sta/Elev= 30
  3984.3 1692.31  4030.6 1689.18  4036.7 1687.29  4066.2 1685.33  4087.1 1681.56
  4173.1 1669.27  4253.0 1666.04  4374.7 1656.02  4410.4 1651.04  4439.9 1648.90
  4496.4 1637.09  4561.5 1630.38  4603.3 1623.16  4747.1 1610.21  4846.7 1604.60
  4926.6 1595.09  4997.9 1590.30  5011.8 1586.94  5024.7 1586.54  5025.0 1586.04
  5029.1 1586.54  5041.7 1587.30  5047.8 1589.81  5088.2 1588.75  5134.0 1591.24
  5234.8 1593.36  5475.2 1601.65  5632.3 1611.82  5732.8 1623.55  5884.7 1649.97
#Mann=6,-1,0
  3984.3    0.16       0  4087.1    0.07       0  5024.7    0.07       0
  5029.1    0.07       0  5088.2   0.035       0  5234.8    0.07       0
Bank Sta=5024.7,5029.1
Exp/Cntr=0.3,0.1

Type RM Length L Ch R = 1,13985,545,545,545
BEGIN DESCRIPTION:
Mapping XS 48b227ed
END DESCRIPTION:
XS GIS Cut Line= 3
      1664185.64      6992309.48      1664275.92      6993194.92
      1664362.73      6994007.46
#Sta/Elev= 30
  4117.1 1684.38  4145.8 1676.54  4160.5 1674.99  4175.9 1669.23  4246.3 1654.68
  4316.7 1645.90  4417.2 1627.70  4427.2 1623.95  4437.3 1622.02  4507.6 1611.20
  4638.3 1600.52  4752.1 1595.98  4850.7 1590.93  4902.0 1586.71  4977.8 1584.87
  4978.1 1584.37  4982.4 1584.87  5055.3 1586.48  5163.5 1590.98  5231.8 1593.16
  5452.7 1601.91  5573.4 1609.13  5614.5 1612.82  5674.0 1621.50  5701.8 1627.42
  5724.3 1630.03  5774.6 1640.92  5794.1 1643.78  5799.2 1643.35  5824.3 1648.90
#Mann=9,-1,0
  4117.1    0.07       0  4752.1   0.035       0  4850.7    0.07       0
  4902.0   0.035       0  4977.8   0.035       0  4982.4   0.035       0
  5055.3    0.07       0  5163.5   0.035       0  5231.8    0.07       0
Bank Sta=4977.8,4982.4
Exp/Cntr=0.3,0.1

Type RM Length L Ch R = 1,13440,798,798,798
BEGIN DESCRIPTION:
Mapping XS bd11198b
END DESCRIPTION:
XS GIS Cut Line= 3
      1663538.93      6992514.32      1663751.61      6993152.39
      1664216.02      6993950.99
#Sta/Elev= 30
  4342.5 1663.26  4405.3 1650.77  4443.6 1643.29  4501.6 1627.91  4564.9 1615.80
  4588.1 1613.07  4628.1 1603.39  4665.0 1599.42  4691.4 1593.51  4715.3 1591.65
  4736.4 1587.33  4835.5 1582.99  4968.3 1580.35  4997.6 1577.05  4997.9 1576.55
  5002.3 1577.05  5044.7 1577.66  5051.1 1580.23  5056.9 1579.30  5066.8 1581.58
  5102.5 1583.76  5109.8 1586.24  5248.9 1595.51  5350.6 1596.76  5446.7 1602.11
  5709.0 1610.39  5819.8 1620.92  5891.0 1633.63  5906.8 1638.34  5938.9 1642.44
#Mann=6,-1,0
  4342.5    0.16       0  4405.3    0.07       0  4588.1    0.16       0
  4835.5    0.07       0  4997.6    0.07       0  5002.3    0.07       0
Bank Sta=4997.6,5002.3
Exp/Cntr=0.3,0.1

Type RM Length L Ch R = 1,12642,476,476,476
BEGIN DESCRIPTION:
Mapping XS a0ffd5dc
END DESCRIPTION:
XS GIS Cut Line= 3
      1662657.90      6993013.52      1663148.31      6993343.36
      1664133.59      6993985.74
#Sta/Elev= 30
  4410.2 1672.58  4426.0 1672.52  4491.1 1663.77  4596.0 1642.83  4635.7 1635.76
  4697.7 1621.54  4728.9 1613.90  4764.9 1608.37  4806.9 1599.52  4851.9 1594.07
  4908.9 1583.11  4944.9 1578.51  4973.1 1571.21  5006.8 1566.98  5007.1 1566.48
  5011.6 1566.98  5017.0 1568.66  5059.2 1569.74  5089.4 1573.83  5140.5 1576.67
  5183.0 1581.07  5348.9 1587.93  5463.5 1594.56  5804.6 1606.60  5928.4 1612.60
  6035.8 1622.07  6079.2 1627.43  6115.4 1633.65  6143.3 1640.47  6177.4 1644.32
#Mann=5,-1,0
  4410.2    0.07       0  4596.0    0.16       0  4697.7    0.07       0
  5006.8    0.07       0  5011.6    0.07       0
Bank Sta=5006.8,5011.6
Exp/Cntr=0.3,0.1

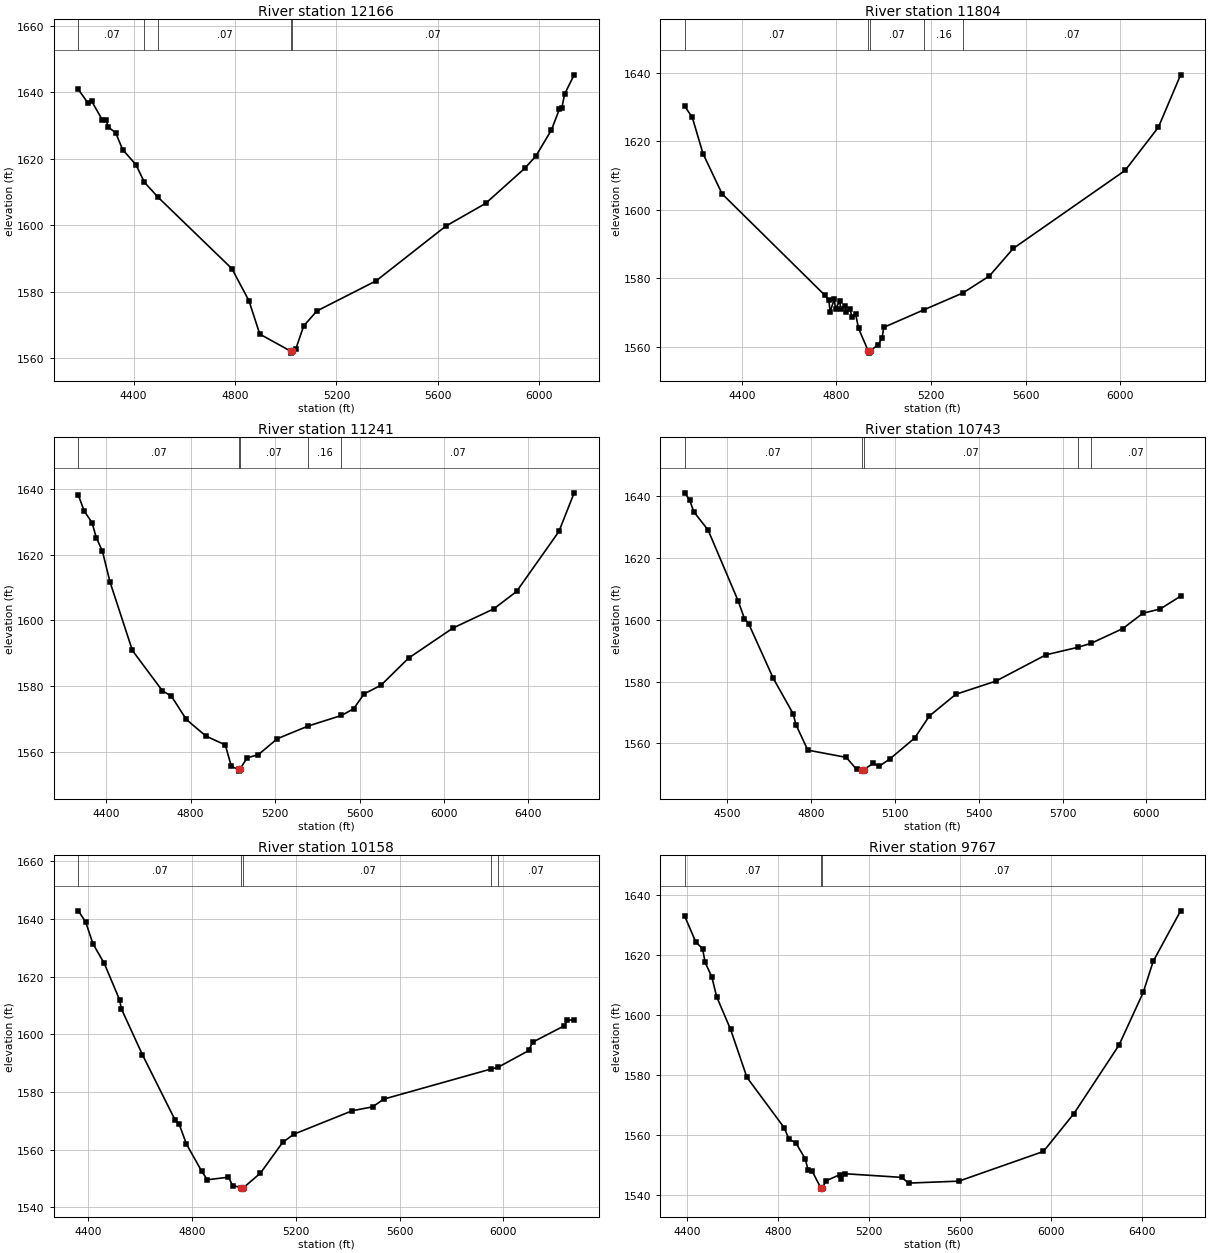
Type RM Length L Ch R = 1,12166,362,362,362
BEGIN DESCRIPTION:
Mapping XS 05fceefe
END DESCRIPTION:
XS GIS Cut Line= 3
      1662245.54      6993326.00      1662948.66      6993747.00
      1664041.20      6994054.82
#Sta/Elev= 30
  4182.4 1640.91  4219.0 1636.97  4234.6 1637.41  4277.4 1631.70  4292.9 1631.68
  4298.8 1629.71  4329.9 1627.81  4357.1 1622.81  4409.6 1618.25  4442.9 1612.97
  4496.9 1608.46  4787.9 1586.98  4854.9 1577.35  4897.7 1567.30  5021.7 1562.08
  5022.0 1561.58  5026.5 1562.08  5039.7 1562.84  5070.9 1569.77  5122.8 1574.26
  5356.2 1583.32  5631.9 1599.83  5787.7 1606.61  5942.1 1617.16  5986.5 1620.90
  6047.4 1628.71  6078.6 1634.93  6088.6 1635.42  6099.4 1639.52  6137.0 1645.30
#Mann=5,-1,0
  4182.4    0.07       0  4442.9    0.16       0  4496.9    0.07       0
  5021.7    0.07       0  5026.5    0.07       0
Bank Sta=5021.7,5026.5
Exp/Cntr=0.3,0.1

Type RM Length L Ch R = 1,11804,563,563,563
BEGIN DESCRIPTION:
Mapping XS cdb6c2bb
END DESCRIPTION:
XS GIS Cut Line= 3
      1661933.01      6993638.49      1662692.59      6994003.08
      1663938.22      6994141.97
#Sta/Elev= 30
  4159.1 1630.19  4190.8 1626.96  4236.1 1616.38  4316.6 1604.64  4751.0 1575.04
  4768.1 1573.51  4773.6 1570.17  4790.7 1573.93  4796.3 1571.00  4813.4 1573.32
  4818.9 1571.08  4836.0 1572.01  4841.6 1570.04  4858.7 1570.94  4864.2 1568.80
  4881.3 1569.54  4893.4 1565.37  4935.4 1558.63  4935.7 1558.13  4940.2 1558.63
  4977.5 1560.64  4993.2 1562.64  5000.1 1565.66  5171.3 1570.82  5335.8 1575.74
  5446.8 1580.66  5547.4 1588.69  6020.3 1611.47  6161.2 1624.10  6255.0 1639.39
#Mann=5,-1,0
  4159.1    0.07       0  4935.4    0.07       0  4940.2    0.07       0
  5171.3    0.16       0  5335.8    0.07       0
Bank Sta=4935.4,4940.2
Exp/Cntr=0.3,0.1

Type RM Length L Ch R = 1,11241,498,498,498
BEGIN DESCRIPTION:
Chimney Creek 1163 25.0
END DESCRIPTION:
XS GIS Cut Line= 3
      1661713.44      6993898.93      1662274.62      6994367.84
      1663886.98      6994256.56
#Sta/Elev= 30
  4268.7 1638.06  4297.0 1633.18  4333.4 1629.73  4354.2 1625.03  4382.9 1620.99
  4418.0 1611.77  4524.7 1590.78  4666.6 1578.52  4709.5 1576.87  4779.8 1569.79
  4872.2 1564.75  4964.6 1562.02  4993.2 1555.47  5028.0 1554.55  5028.4 1554.05
  5033.0 1554.55  5067.9 1558.11  5120.7 1559.05  5210.7 1563.92  5358.0 1567.81
  5514.4 1571.00  5571.7 1573.01  5621.9 1577.57  5702.1 1580.22  5832.4 1588.47
  6042.9 1597.63  6235.2 1603.44  6343.6 1608.75  6544.0 1627.01  6616.2 1638.78
#Mann=5,-1,0
  4268.7    0.07       0  5028.0    0.07       0  5033.0    0.07       0
  5358.0    0.16       0  5514.4    0.07       0
Bank Sta=5028,5033
Exp/Cntr=0.3,0.1

Type RM Length L Ch R = 1,10743,585,585,585
BEGIN DESCRIPTION:
Chimney Creek 1163 24.0
END DESCRIPTION:
XS GIS Cut Line= 3
      1661562.23      6993976.54      1661899.02      6994535.64
      1662402.49      6995539.01
#Sta/Elev= 30
  4347.3 1640.93  4364.4 1638.61  4380.0 1634.75  4430.7 1628.91  4539.2 1605.84
  4560.6 1600.34  4576.1 1598.62  4664.2 1581.01  4735.3 1569.57  4745.0 1566.10
  4787.7 1557.84  4925.6 1555.50  4962.5 1551.60  4980.0 1551.56  4980.5 1551.06
  4987.7 1551.56  5021.9 1553.53  5044.3 1552.71  5081.0 1554.95  5170.5 1561.76
  5223.0 1568.86  5317.9 1575.88  5461.4 1580.14  5640.4 1588.62  5755.4 1591.06
  5802.3 1592.35  5915.4 1597.08  5988.0 1602.07  6049.4 1603.41  6122.6 1607.56
#Mann=5,-1,0
  4347.3    0.07       0  4980.0    0.07       0  4987.7    0.07       0
  5755.4    0.16       0  5802.3    0.07       0
Bank Sta=4980,4987.7
Exp/Cntr=0.3,0.1

Type RM Length L Ch R = 1,10158,391,391,391
BEGIN DESCRIPTION:
Mapping XS 446f4929
END DESCRIPTION:
XS GIS Cut Line= 3
      1661162.93      6994313.35      1661471.96      6994875.86
      1662419.84      6995719.58
#Sta/Elev= 30
  4362.1 1642.80  4390.2 1638.98  4418.5 1631.36  4462.1 1624.57  4521.8 1611.81
  4527.5 1608.94  4609.0 1592.94  4734.0 1570.47  4750.1 1569.02  4778.2 1562.05
  4837.3 1552.58  4859.1 1549.59  4940.6 1550.47  4956.7 1547.59  4990.7 1546.84
  4991.2 1546.34  4998.4 1546.84  5064.0 1551.90  5149.3 1562.52  5191.9 1565.35
  5418.5 1573.53  5496.3 1574.85  5538.9 1577.53  5953.6 1588.00  5978.5 1588.52
  6098.3 1594.39  6112.5 1597.25  6232.9 1602.86  6247.2 1604.85  6272.9 1605.03
#Mann=5,-1,0
  4362.1    0.07       0  4990.7    0.07       0  4998.4    0.07       0
  5953.6    0.16       0  5978.5    0.07       0
Bank Sta=4990.7,4998.4
Exp/Cntr=0.3,0.1

Type RM Length L Ch R = 1,9767,873,873,873
BEGIN DESCRIPTION:
Mapping XS 34030aec
END DESCRIPTION:
XS GIS Cut Line= 3
      1661041.40      6994521.69      1661176.82      6995122.39
      1661024.04      6996677.93
#Sta/Elev= 30
  4389.5 1632.73  4437.0 1624.31  4467.7 1621.91  4478.6 1617.45  4508.7 1612.46
  4529.2 1606.01  4590.7 1595.08  4662.5 1579.10  4826.5 1562.31  4847.0 1558.55
  4877.8 1557.25  4918.8 1551.94  4931.5 1548.19  4949.5 1547.79  4986.6 1542.38
  4987.1 1541.88  4994.4 1542.38  5010.9 1544.67  5070.6 1546.69  5075.6 1545.15
  5091.3 1547.02  5342.5 1545.79  5372.6 1543.89  5593.7 1544.54  5965.5 1554.43
  6099.6 1567.06  6297.1 1589.78  6403.8 1607.37  6447.8 1617.76  6568.3 1634.57
#Mann=3,-1,0
  4389.5    0.07       0  4986.6    0.07       0  4994.4    0.07       0
Bank Sta=4986.6,4994.4
Exp/Cntr=0.3,0.1

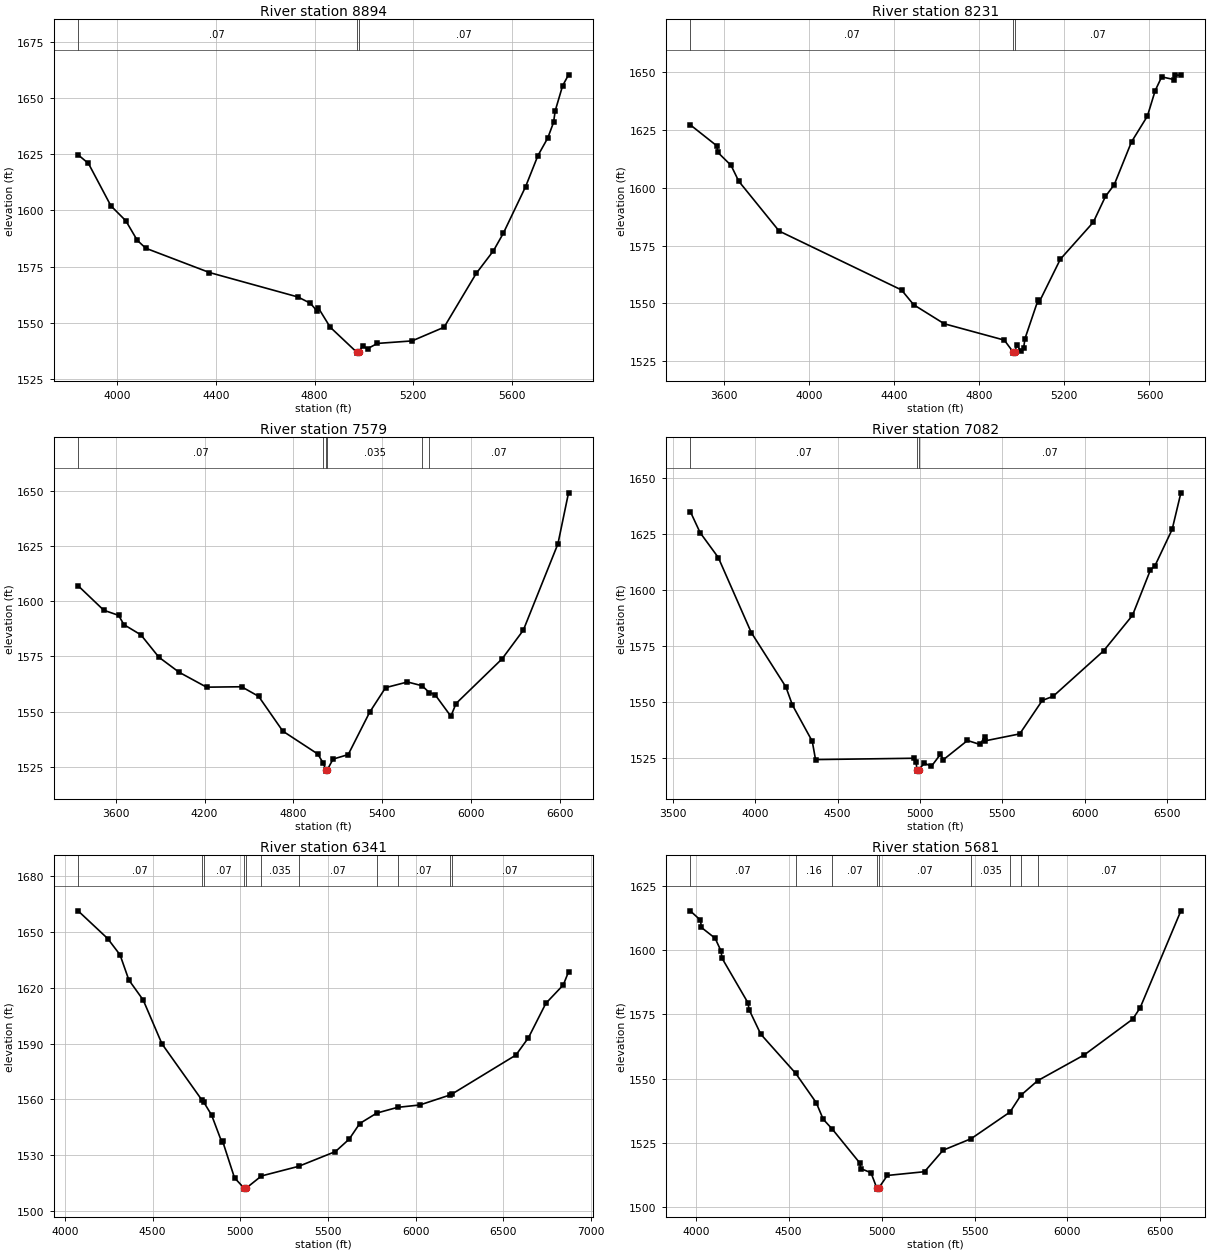
Type RM Length L Ch R = 1,8894,663,663,663
BEGIN DESCRIPTION:
Mapping XS 9d98dbaf
END DESCRIPTION:
XS GIS Cut Line= 3
      1660912.93      6994636.30      1660753.21      6995792.53
      1660749.74      6996612.01
#Sta/Elev= 30
  3842.2 1624.75  3884.3 1620.88  3975.2 1602.04  4035.7 1595.38  4082.0 1586.70
  4116.5 1583.18  4374.5 1572.37  4732.3 1561.52  4782.7 1558.75  4810.8 1555.20
  4815.8 1556.58  4863.5 1548.07  4970.1 1537.03  4970.6 1536.53  4979.0 1537.03
  4994.7 1539.59  5014.9 1538.52  5054.9 1540.85  5194.9 1541.96  5324.9 1548.05
  5454.9 1571.96  5524.9 1582.07  5564.9 1589.86  5654.9 1610.53  5704.9 1624.37
  5744.9 1632.23  5768.2 1639.13  5774.9 1644.26  5804.9 1655.43  5828.9 1660.30
#Mann=3,-1,0
  3842.2    0.07       0  4970.1    0.07       0  4979.0    0.07       0
Bank Sta=4970.1,4979
Exp/Cntr=0.3,0.1

Type RM Length L Ch R = 1,8231,652,652,652
BEGIN DESCRIPTION:
Mapping XS 75561221
END DESCRIPTION:
XS GIS Cut Line= 3
      1660833.09      6994504.29      1660180.29      6995934.89
      1660294.88      6996657.16
#Sta/Elev= 30
  3443.7 1627.17  3567.4 1618.16  3572.9 1615.27  3634.6 1609.69  3670.5 1602.87
  3860.3 1581.31  4435.2 1555.84  4492.2 1549.46  4635.9 1541.23  4917.9 1534.17
  4959.4 1529.04  4959.9 1528.54  4968.4 1529.04  4975.6 1532.05  4998.0 1529.28
  5008.6 1530.64  5015.2 1534.83  5076.6 1551.51  5081.7 1550.57  5181.3 1569.15
  5335.9 1585.10  5393.1 1596.26  5434.5 1601.37  5515.5 1619.86  5590.1 1630.98
  5626.9 1642.05  5657.4 1647.96  5714.6 1646.80  5719.7 1648.84  5747.5 1648.56
#Mann=3,-1,0
  3443.7    0.07       0  4959.4    0.07       0  4968.4    0.07       0
Bank Sta=4959.4,4968.4
Exp/Cntr=0.3,0.1

Type RM Length L Ch R = 1,7579,497,497,497
BEGIN DESCRIPTION:
Mapping XS dc8be7c7
END DESCRIPTION:
XS GIS Cut Line= 3
      1660811.90      6994132.10      1659830.99      6995473.26
      1659215.16      6997004.14
#Sta/Elev= 30
  3346.0 1607.14  3519.6 1595.99  3620.0 1593.67  3655.5 1589.46  3770.5 1584.81
  3891.8 1574.67  4027.7 1567.87  4213.7 1561.07  4450.0 1561.26  4565.0 1556.92
  4728.5 1541.12  4964.3 1530.74  5001.6 1526.59  5018.9 1523.46  5019.4 1522.96
  5028.0 1523.46  5067.9 1528.42  5170.0 1530.46  5314.5 1549.64  5422.3 1560.85
  5570.4 1563.43  5668.7 1561.72  5718.8 1558.56  5755.8 1557.74  5863.3 1547.86
  5898.2 1553.65  6209.1 1573.92  6352.3 1586.91  6586.1 1626.12  6657.7 1649.29
#Mann=6,-1,0
  3346.0    0.07       0  5001.6   0.035       0  5018.9    0.07       0
  5028.0   0.035       0  5668.7    0.16       0  5718.8    0.07       0
Bank Sta=5018.9,5028
Exp/Cntr=0.3,0.1

Type RM Length L Ch R = 1,7082,741,741,741
BEGIN DESCRIPTION:
Mapping XS faa1b083
END DESCRIPTION:
XS GIS Cut Line= 3
      1659375.26      6993889.04      1659401.30      6995295.30
      1658945.56      6996797.07
#Sta/Elev= 30
  3607.3 1634.93  3666.3 1625.58  3776.3 1614.49  3976.3 1580.96  4186.4 1556.63
  4226.4 1548.48  4346.4 1532.33  4366.4 1524.14  4966.5 1524.74  4976.5 1523.09
  4981.7 1519.48  4982.2 1518.98  4991.2 1519.48  5027.1 1522.57  5068.9 1521.08
  5124.0 1526.48  5142.0 1524.09  5288.3 1532.68  5364.7 1530.89  5392.3 1534.34
  5397.6 1532.55  5605.4 1535.63  5742.2 1550.59  5808.0 1552.43  6113.9 1572.73
  6289.4 1588.62  6398.5 1608.95  6426.2 1610.85  6530.1 1627.04  6583.2 1643.41
#Mann=3,-1,0
  3607.3    0.07       0  4981.7    0.07       0  4991.2    0.07       0
Bank Sta=4981.7,4991.2
Exp/Cntr=0.3,0.1

Type RM Length L Ch R = 1,6341,660,660,660
BEGIN DESCRIPTION:
Mapping XS 120d92ee
END DESCRIPTION:
XS GIS Cut Line= 3
      1659032.37      6993819.65      1658949.91      6994752.77
      1658563.62      6996571.35
#Sta/Elev= 30
  4075.4 1661.21  4244.4 1646.31  4314.7 1637.60  4364.9 1624.12  4446.7 1613.36
  4553.7 1589.84  4782.0 1559.63  4790.9 1558.74  4836.7 1551.63  4894.7 1537.14
  4899.7 1537.56  4967.2 1517.98  5022.1 1512.42  5022.6 1511.92  5033.4 1512.42
  5120.6 1518.98  5333.1 1524.16  5542.6 1532.07  5620.7 1538.71  5681.2 1547.12
  5778.3 1552.72  5896.7 1555.78  6023.4 1557.06  6195.0 1562.39  6207.1 1562.94
  6571.4 1583.84  6643.0 1593.16  6742.2 1611.60  6841.5 1621.45  6871.3 1628.50
#Mann=11,-1,0
  4075.4    0.07       0  4782.0    0.16       0  4790.9    0.07       0
  5022.1    0.07       0  5033.4    0.07       0  5120.6   0.035       0
  5333.1    0.07       0  5778.3   0.035       0  5896.7    0.07       0
  6195.0   0.035       0  6207.1    0.07       0
Bank Sta=5022.1,5033.4
Exp/Cntr=0.3,0.1

Type RM Length L Ch R = 1,5681,838,838,838
BEGIN DESCRIPTION:
Mapping XS c15ea539
END DESCRIPTION:
XS GIS Cut Line= 3
      1657980.86      6993923.45      1658341.11      6994891.37
      1658358.47      6996497.29
#Sta/Elev= 30
  3971.5 1615.17  4025.4 1611.64  4030.7 1608.78  4104.4 1604.59  4136.1 1599.62
  4141.4 1596.84  4280.5 1579.53  4287.8 1576.71  4349.8 1567.28  4537.7 1552.03
  4648.6 1540.58  4685.8 1534.17  4735.1 1530.29  4882.2 1517.19  4887.5 1514.97
  4942.9 1513.35  4973.7 1507.47  4974.2 1506.97  4985.0 1507.47  5030.9 1512.29
  5230.9 1513.75  5330.9 1522.11  5481.6 1526.59  5690.8 1536.96  5749.3 1543.48
  5839.4 1549.15  6091.0 1559.23  6351.0 1573.11  6391.0 1577.52  6610.3 1615.26
#Mann=9,-1,0
  3971.5    0.07       0  4537.7    0.16       0  4735.1    0.07       0
  4973.7    0.07       0  4985.0    0.07       0  5481.6   0.035       0
  5690.8    0.07       0  5749.3   0.035       0  5839.4    0.07       0
Bank Sta=4973.7,4985
Exp/Cntr=0.3,0.1

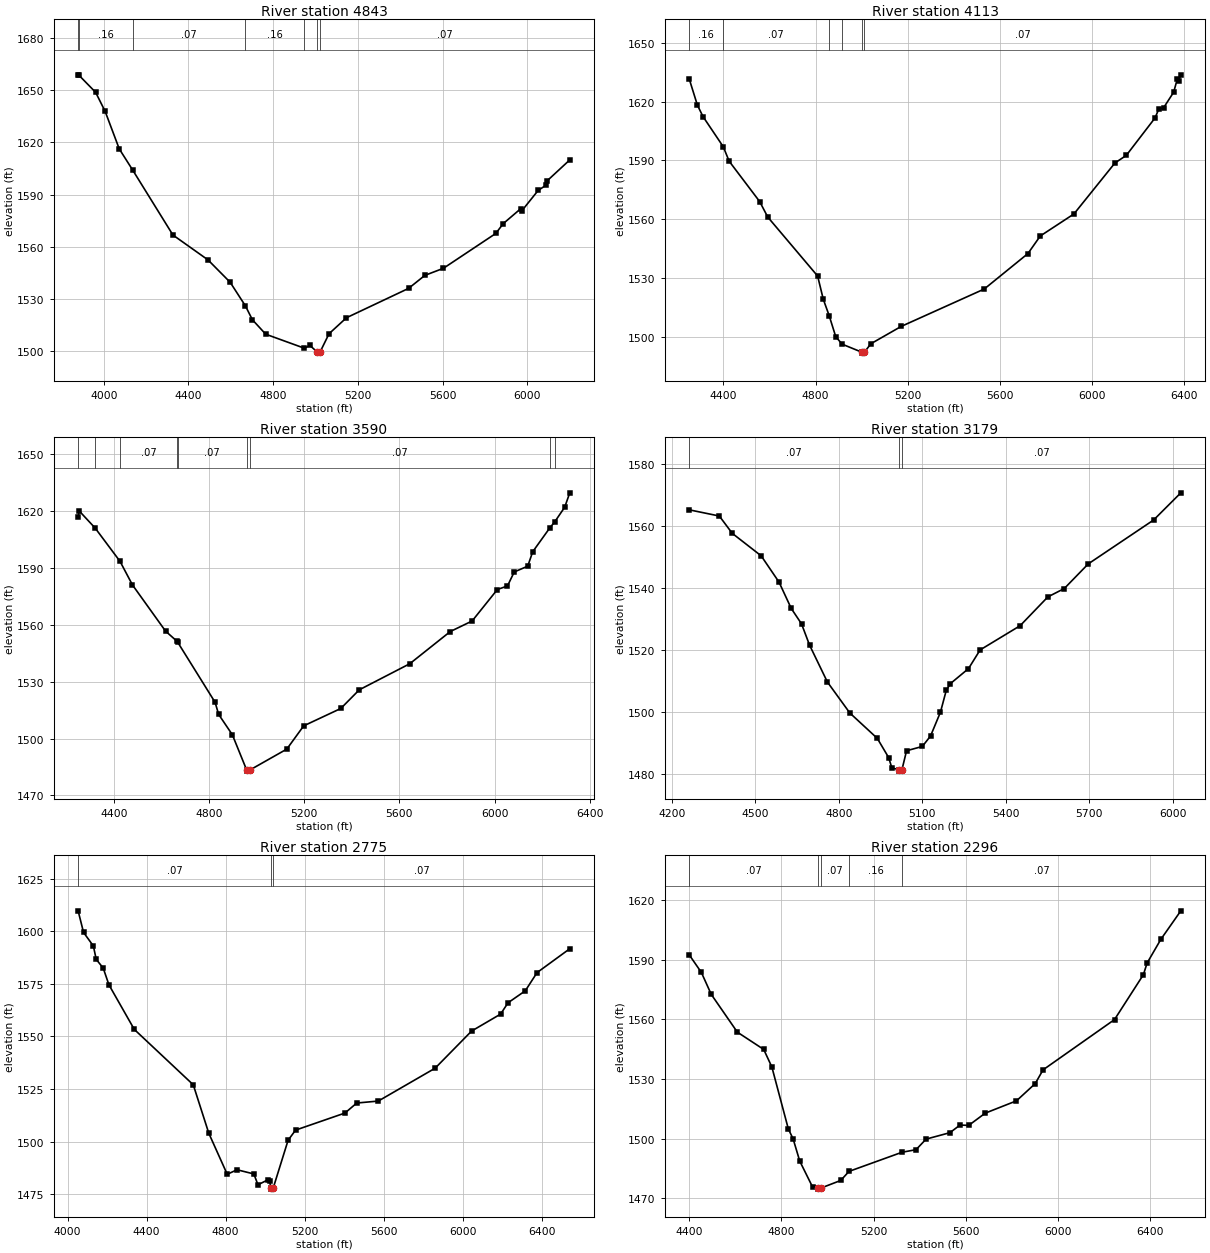
Type RM Length L Ch R = 1,4843,730,730,730
BEGIN DESCRIPTION:
Mapping XS 482ea88d
END DESCRIPTION:
XS GIS Cut Line= 3
      1657334.17      6994218.63      1657655.35      6995299.35
      1657946.14      6996458.18
#Sta/Elev= 30
  3878.8 1658.83  3883.6 1658.46  3961.6 1648.76  4006.6 1637.76  4073.0 1616.27
  4137.5 1603.89  4326.7 1566.73  4492.2 1552.45  4597.0 1539.57  4669.1 1525.98
  4701.9 1518.04  4764.9 1509.73  4948.0 1501.65  4973.5 1503.29  5009.3 1499.35
  5009.8 1498.85  5021.1 1499.35  5064.0 1510.00  5146.3 1519.19  5439.6 1536.06
  5516.8 1543.56  5604.3 1547.62  5851.3 1567.62  5887.3 1573.35  5969.6 1581.90
  5974.7 1580.69  6051.9 1592.40  6087.4 1595.25  6093.1 1597.78  6201.0 1609.92
#Mann=7,-1,0
  3878.8    0.07       0  3883.6    0.16       0  4137.5    0.07       0
  4669.1    0.16       0  4948.0    0.07       0  5009.3    0.07       0
  5021.1    0.07       0
Bank Sta=5009.3,5021.1
Exp/Cntr=0.3,0.1

Type RM Length L Ch R = 1,4113,523,523,523
BEGIN DESCRIPTION:
Mapping XS 138f535f
END DESCRIPTION:
XS GIS Cut Line= 3
      1656696.15      6994542.13      1656973.93      6995245.25
      1657646.68      6996447.52
#Sta/Elev= 30
  4251.8 1631.72  4287.2 1618.33  4311.6 1612.45  4399.5 1597.05  4425.2 1589.63
  4557.7 1569.00  4592.8 1561.08  4809.2 1530.96  4833.6 1519.14  4859.2 1510.74
  4887.7 1500.01  4915.3 1496.16  5000.6 1492.07  5001.1 1491.57  5012.5 1492.07
  5040.2 1496.36  5171.4 1505.19  5532.3 1524.32  5721.8 1542.43  5775.5 1551.42
  5921.6 1562.68  6099.6 1588.73  6148.8 1592.60  6273.3 1611.70  6289.3 1616.10
  6311.0 1616.99  6354.4 1624.89  6370.3 1631.69  6376.1 1630.62  6385.5 1633.76
#Mann=6,-1,0
  4251.8    0.16       0  4399.5    0.07       0  4859.2    0.16       0
  4915.3    0.07       0  5000.6    0.07       0  5012.5    0.07       0
Bank Sta=5000.6,5012.5
Exp/Cntr=0.3,0.1

Type RM Length L Ch R = 1,3590,411,411,411
BEGIN DESCRIPTION:
Mapping XS 3fc6ce09
END DESCRIPTION:
XS GIS Cut Line= 3
      1656127.56      6994828.57      1656539.90      6995462.26
      1657428.33      6996424.37
#Sta/Elev= 30
  4250.2 1616.74  4255.1 1619.76  4322.2 1610.72  4426.3 1593.25  4478.4 1580.87
  4617.4 1556.56  4665.0 1551.26  4668.6 1550.68  4825.6 1519.07  4840.7 1512.67
  4898.1 1502.00  4958.6 1483.33  4959.1 1482.83  4970.5 1483.33  5127.0 1494.43
  5197.9 1506.66  5353.8 1515.81  5431.5 1525.64  5643.6 1539.36  5813.7 1556.31
  5905.6 1561.87  6011.6 1578.44  6054.1 1580.31  6082.5 1587.68  6139.2 1590.73
  6160.2 1598.33  6232.5 1610.97  6252.6 1614.06  6294.6 1621.78  6315.8 1629.34
#Mann=9,-1,0
  4250.2    0.07       0  4322.2    0.16       0  4426.3    0.07       0
  4665.0    0.16       0  4668.6    0.07       0  4958.6    0.07       0
  4970.5    0.07       0  6232.5    0.16       0  6252.6    0.07       0
Bank Sta=4958.6,4970.5
Exp/Cntr=0.3,0.1

Type RM Length L Ch R = 1,3179,404,404,404
BEGIN DESCRIPTION:
Mapping XS 1fc4828f
END DESCRIPTION:
XS GIS Cut Line= 3
      1655926.37      6995043.25      1656224.97      6995713.36
      1657064.49      6996313.51
#Sta/Elev= 30
  4263.0 1565.10  4371.2 1563.10  4417.7 1557.51  4521.5 1550.26  4585.7 1541.77
  4629.5 1533.29  4666.4 1528.33  4695.2 1521.48  4759.3 1509.57  4840.0 1499.57
  4938.4 1491.41  4979.4 1485.19  4990.8 1481.86  5015.3 1481.33  5015.8 1480.83
  5027.2 1481.33  5043.6 1487.40  5100.2 1488.79  5129.7 1492.15  5165.3 1499.84
  5186.2 1506.88  5200.9 1509.04  5266.0 1513.89  5307.8 1519.92  5451.5 1527.73
  5551.1 1537.02  5610.1 1539.72  5696.1 1547.66  5930.9 1561.82  6028.6 1570.58
#Mann=3,-1,0
  4263.0    0.07       0  5015.3    0.07       0  5027.2    0.07       0
Bank Sta=5015.3,5027.2
Exp/Cntr=0.3,0.1

Type RM Length L Ch R = 1,2775,479,479,479
BEGIN DESCRIPTION:
Mapping XS c3b25022
END DESCRIPTION:
XS GIS Cut Line= 3
      1655158.98      6995355.71      1655912.47      6995942.53
      1657256.24      6996682.12
#Sta/Elev= 30
  4053.5 1609.65  4080.9 1599.40  4130.7 1592.95  4145.1 1586.59  4180.4 1582.49
  4209.4 1574.52  4337.8 1553.34  4636.4 1527.03  4715.1 1504.00  4808.3 1484.53
  4858.1 1486.68  4943.1 1484.69  4963.9 1479.54  5013.3 1481.86  5022.8 1481.52
  5029.1 1477.98  5029.6 1477.48  5041.1 1477.98  5116.5 1500.70  5154.4 1505.51
  5404.4 1513.62  5464.0 1518.37  5573.0 1519.30  5860.8 1534.91  6045.5 1552.55
  6192.2 1560.60  6230.1 1565.99  6317.2 1571.66  6376.9 1580.32  6542.4 1591.64
#Mann=3,-1,0
  4053.5    0.07       0  5029.1    0.07       0  5041.1    0.07       0
Bank Sta=5029.1,5041.1
Exp/Cntr=0.3,0.1

Type RM Length L Ch R = 1,2296,431,431,431
BEGIN DESCRIPTION:
Mapping XS 21b723cf
END DESCRIPTION:
XS GIS Cut Line= 3
      1655065.27      6995782.82      1655527.05      6996171.69
      1656259.71      6997512.01
#Sta/Elev= 30
  4400.5 1592.37  4453.2 1583.53  4496.1 1572.48  4609.3 1553.50  4723.6 1544.81
  4758.8 1536.02  4830.3 1504.85  4851.1 1499.83  4879.7 1488.71  4936.2 1475.48
  4957.9 1475.12  4958.4 1474.62  4970.7 1475.12  5057.4 1478.98  5093.2 1483.53
  5323.3 1493.16  5383.7 1494.43  5427.3 1499.75  5530.8 1502.99  5574.4 1506.81
  5612.3 1506.66  5683.8 1512.80  5819.2 1518.99  5900.3 1527.63  5934.5 1534.56
  6244.2 1559.82  6369.4 1582.39  6385.5 1588.24  6445.3 1600.19  6531.7 1614.47
#Mann=5,-1,0
  4400.5    0.07       0  4957.9    0.07       0  4970.7    0.07       0
  5093.2    0.16       0  5323.3    0.07       0
Bank Sta=4957.9,4970.7
Exp/Cntr=0.3,0.1