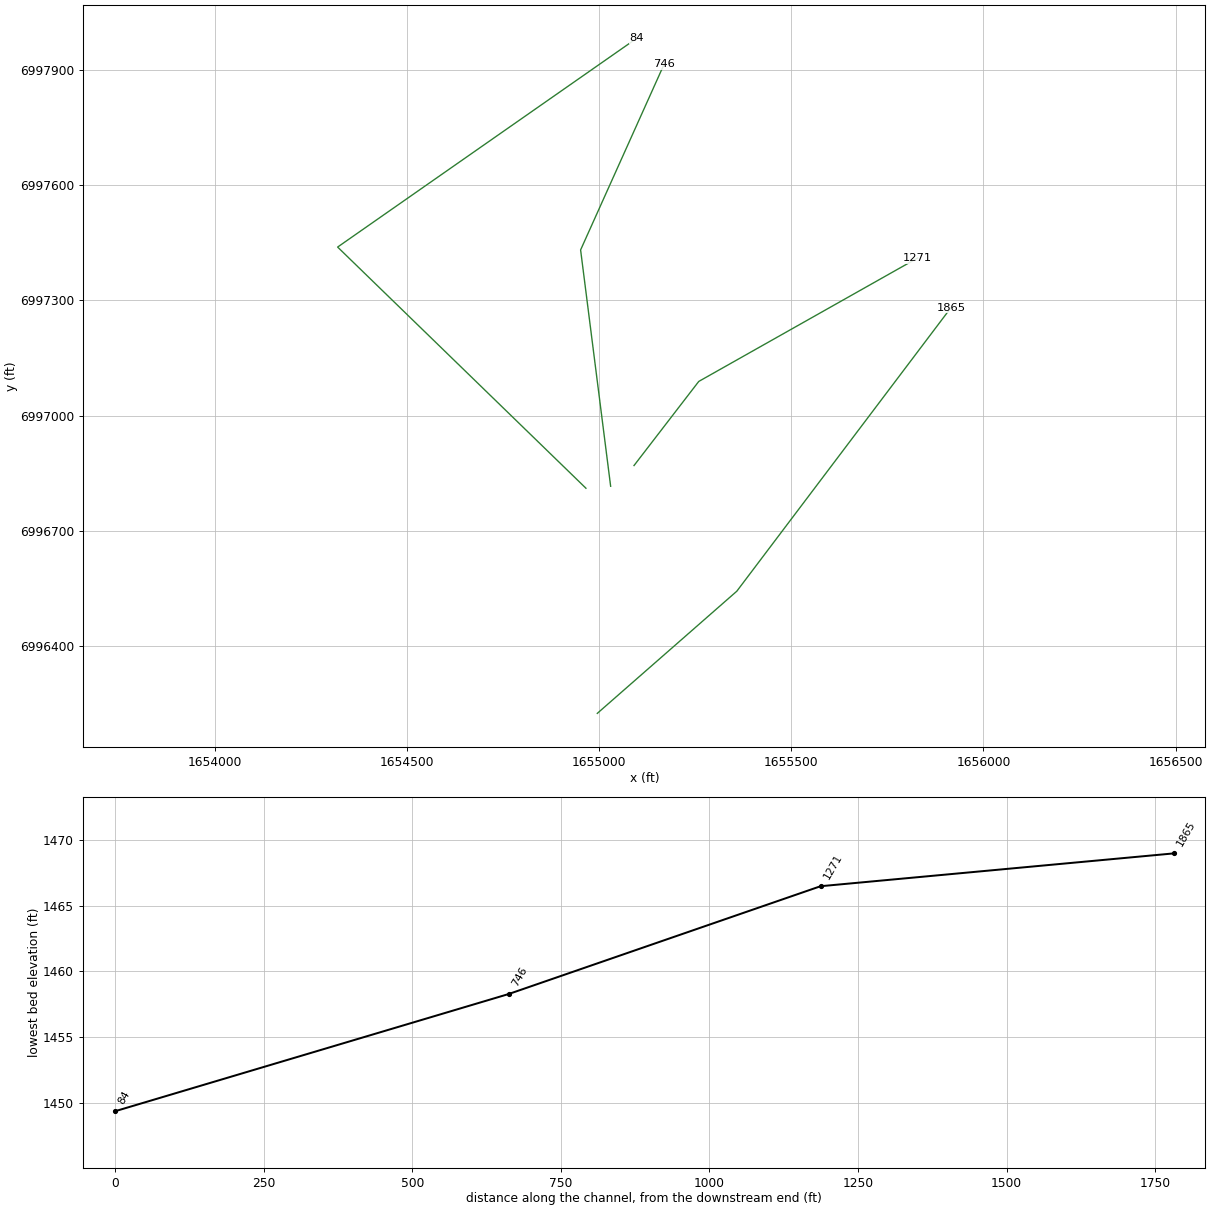
HEC-RAS study Chimney Creek 1163.prj: Chimney Creek 1163 Base Level Engineering

--- Chimney Creek 1163.g01 (geometry) --- (continued)

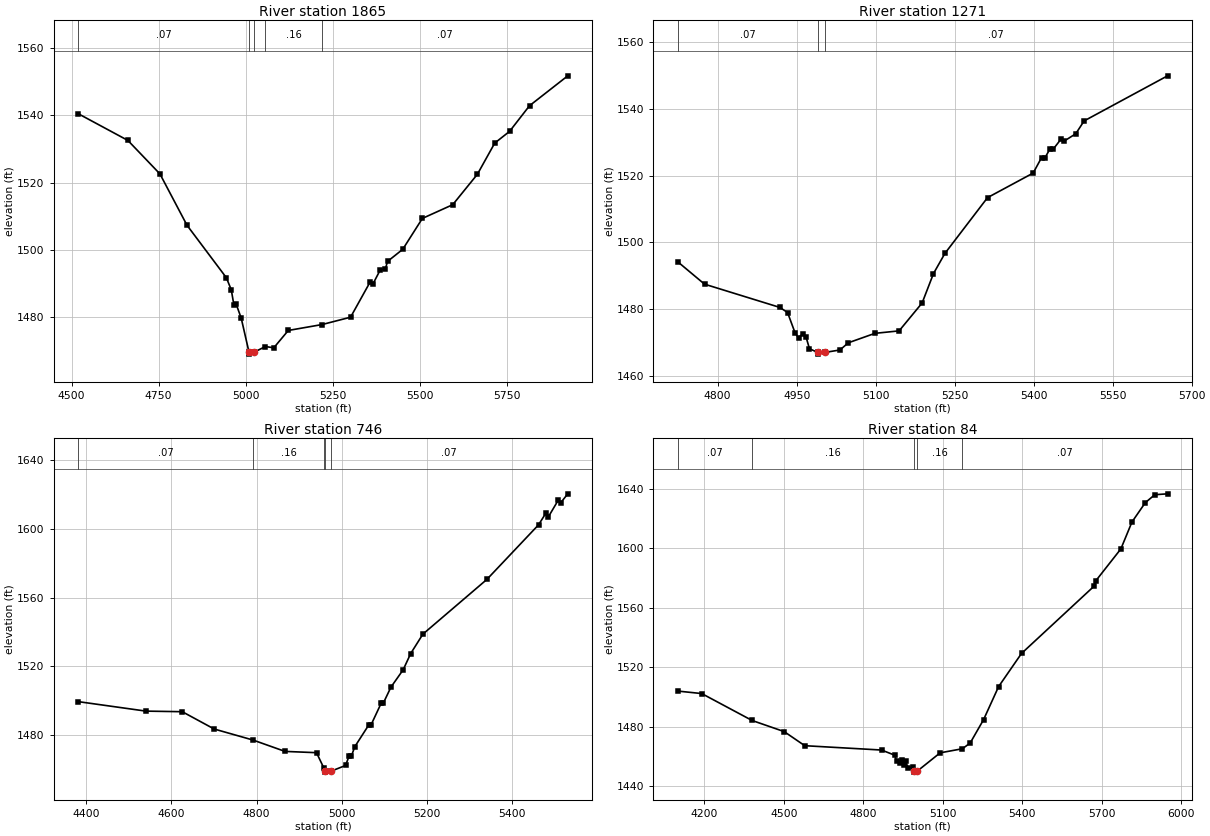
Type RM Length L Ch R = 1,1865,594,594,594
BEGIN DESCRIPTION:
Mapping XS cf43bb55
END DESCRIPTION:
XS GIS Cut Line= 3
      1654995.55      6996225.73      1655358.42      6996543.45
      1655915.73      6997281.33
#Sta/Elev= 30
  4518.7 1540.52  4661.9 1532.54  4754.0 1522.58  4831.8 1507.31  4944.8 1491.72
  4959.0 1488.11  4966.6 1483.53  4973.2 1483.80  4987.5 1479.70  5010.1 1469.49
  5010.6 1468.99  5023.0 1469.49  5057.1 1471.25  5081.1 1470.87  5122.8 1476.03
  5219.5 1477.78  5301.7 1479.97  5358.0 1490.46  5366.3 1489.92  5387.1 1494.06
  5401.6 1494.30  5407.9 1496.56  5451.6 1500.16  5508.0 1509.35  5595.2 1513.43
  5666.0 1522.47  5715.9 1531.75  5758.6 1535.24  5815.8 1542.86  5925.7 1551.75
#Mann=5,-1,0
  4518.7    0.07       0  5010.1    0.07       0  5023.0    0.07       0
  5057.1    0.16       0  5219.5    0.07       0
Bank Sta=5010.1,5023
Exp/Cntr=0.3,0.1

Type RM Length L Ch R = 1,1271,525,525,525
BEGIN DESCRIPTION:
Mapping XS 219a4c70
END DESCRIPTION:
XS GIS Cut Line= 3
      1655091.03      6996870.27      1655259.46      6997089.05
      1655828.92      6997410.24
#Sta/Elev= 30
  4724.3 1494.15  4775.0 1487.46  4918.2 1480.48  4932.7 1478.96  4947.2 1472.76
  4953.5 1471.42  4961.2 1472.55  4968.0 1471.51  4974.3 1468.11  4990.1 1466.99
  4990.6 1466.49  5003.0 1466.99  5032.1 1467.73  5048.1 1469.89  5098.6 1472.72
  5144.5 1473.46  5188.2 1481.82  5209.8 1490.64  5231.5 1496.68  5312.4 1513.39
  5399.0 1520.75  5414.9 1525.35  5420.7 1525.15  5430.9 1527.94  5436.6 1527.82
  5452.5 1531.04  5458.3 1530.37  5479.9 1532.53  5495.8 1536.38  5654.2 1549.89
#Mann=3,-1,0
  4724.3    0.07       0  4990.1    0.07       0  5003.0    0.07       0
Bank Sta=4990.1,5003
Exp/Cntr=0.3,0.1

Type RM Length L Ch R = 1,746,662,662,662
BEGIN DESCRIPTION:
Mapping XS acc5dd3d
END DESCRIPTION:
XS GIS Cut Line= 3
      1655030.30      6996816.45      1654952.17      6997431.07
      1655169.04      6997913.39
#Sta/Elev= 30
  4381.5 1499.39  4540.9 1493.84  4625.9 1493.50  4700.8 1483.40  4791.8 1476.98
  4866.9 1470.35  4940.7 1469.61  4958.1 1460.58  4961.2 1458.77  4961.7 1458.27
  4974.2 1458.77  5008.7 1462.14  5017.2 1467.64  5022.6 1467.73  5030.6 1473.14
  5063.5 1485.86  5068.9 1485.97  5092.1 1498.31  5097.6 1498.62  5115.3 1507.85
  5143.9 1517.94  5161.6 1527.43  5190.2 1538.74  5340.1 1570.61  5461.4 1602.47
  5479.1 1609.50  5484.5 1607.14  5507.7 1616.90  5513.2 1615.29  5529.9 1620.54
#Mann=5,-1,0
  4381.5    0.07       0  4791.8    0.16       0  4958.1    0.07       0
  4961.2    0.07       0  4974.2    0.07       0
Bank Sta=4961.2,4974.2
Exp/Cntr=0.3,0.1

Type RM Length L Ch R = 1,84,0,0,0
BEGIN DESCRIPTION:
Chimney Creek 1163 1.0
END DESCRIPTION:
XS GIS Cut Line= 3
      1654966.05      6996811.28      1654320.22      6997438.53
      1655097.99      6997981.41
#Sta/Elev= 30
  4099.7 1503.83  4190.0 1502.16  4380.3 1484.05  4501.3 1476.58  4579.0 1467.11
  4868.9 1464.19  4918.5 1460.73  4925.5 1457.00  4939.6 1455.56  4946.8 1457.75
  4953.7 1454.35  4960.9 1456.54  4967.9 1452.37  4989.2 1452.50  4989.5 1449.84
  4990.0 1449.34  5002.5 1449.84  5090.1 1462.32  5174.1 1465.06  5203.5 1468.93
  5254.1 1484.66  5310.8 1506.85  5397.2 1529.12  5671.1 1574.35  5677.2 1577.86
  5772.3 1599.41  5814.2 1617.51  5864.7 1630.54  5900.5 1635.85  5948.5 1636.44
#Mann=5,-1,0
  4099.7    0.07       0  4380.3    0.16       0  4989.5    0.07       0
  5002.5    0.16       0  5174.1    0.07       0
Bank Sta=4989.5,5002.5
Exp/Cntr=0.3,0.1

Chan Stop Cuts=-1