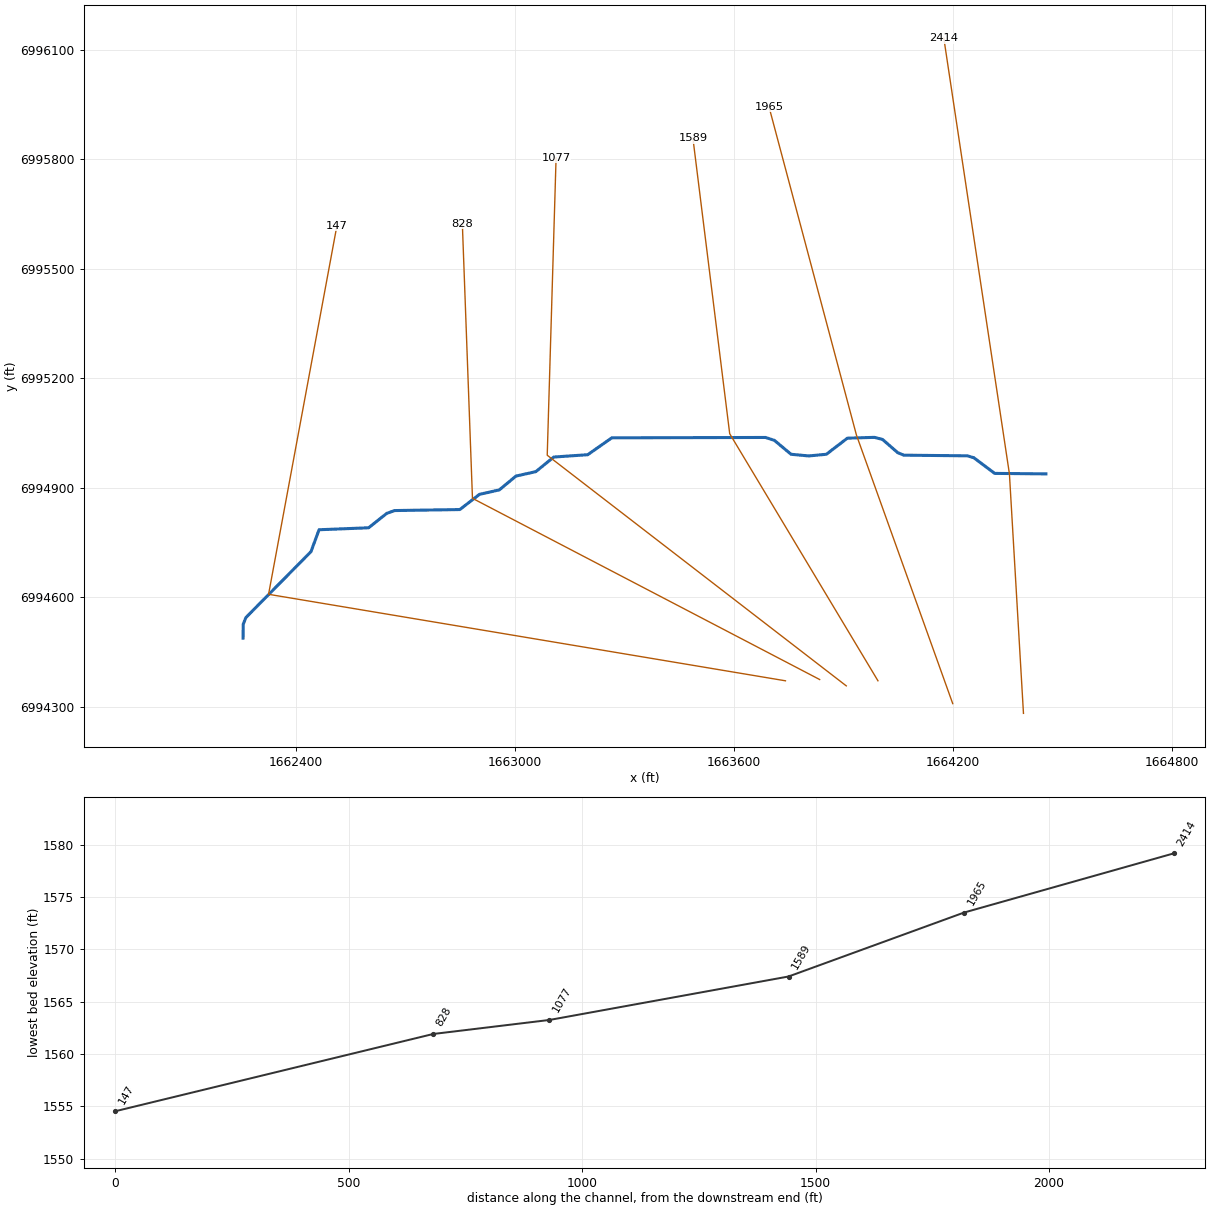
--- Chimney Creek 1164.prj (project) ---

Proj Title=Chimney Creek 1164 Base Level Engineering
Current Plan=p01
Default Exp/Contr=0.3,0.1
English Units
Geom File=g01
Flow File=f01
Plan File=p01
BEGIN DESCRIPTION:
Chimney Creek 1164
END DESCRIPTION:

--- Chimney Creek 1164.p01 (plan) ---

Plan Title=Multiple Run
Short Identifier=Multiple
Geom File=g01
Flow File=f01
Subcritical Flow
K Sum by GR= 0
Std Step Tol= 0.01
Critical Tol= 0.01
Num of Std Step Trials= 20
Max Error Tol= 0.3
Flow Tol Ratio= 0.001
Split Flow NTrial= 30
Split Flow Tol= 0.02
Split Flow Ratio= 0.02
Log Output Level= 0
Friction Slope Method= 1
Unsteady Friction Slope Method= 2
Unsteady Bridges Friction Slope Method= 1
Parabolic Critical Depth
Global Vel Dist=  1 , 1 , 1
Global Log Level= 0
CheckData=True
Encroach Param= -1, 0, 0, 0
BEGIN DESCRIPTION:
Multiple Run
END DESCRIPTION:

--- Chimney Creek 1164.f01 (steady flow) ---

Flow Title=Multiple
Number of Profiles=7
Profile Names=10-year,25-year,50-year,1pct_min,100-year,1pct_plu,500-year
River Rch & RM= Chimney Creek 11,Reach-1,2414
     336     478     599     374     746    1489    1173
Boundary for River Rch & Prof#=Chimney Creek 11,Reach-1,1
Up Type=0
Dn Type=3
Dn Slope=0.005
Boundary for River Rch & Prof#=Chimney Creek 11,Reach-1,2
Up Type=0
Dn Type=3
Dn Slope=0.005
Boundary for River Rch & Prof#=Chimney Creek 11,Reach-1,3
Up Type=0
Dn Type=3
Dn Slope=0.005
Boundary for River Rch & Prof#=Chimney Creek 11,Reach-1,4
Up Type=0
Dn Type=3
Dn Slope=0.005
Boundary for River Rch & Prof#=Chimney Creek 11,Reach-1,5
Up Type=0
Dn Type=3
Dn Slope=0.005
Boundary for River Rch & Prof#=Chimney Creek 11,Reach-1,6
Up Type=0
Dn Type=3
Dn Slope=0.005
Boundary for River Rch & Prof#=Chimney Creek 11,Reach-1,7
Up Type=0
Dn Type=3
Dn Slope=0.005

--- Chimney Creek 1164.g01 (geometry) ---

Geom Title=Existing Conditions

River Reach=Chimney Creek 11,Reach-1
Reach XY= 30
      1664455.00      6994938.00      1664314.64      6994939.33
      1664257.34      6994982.26      1664239.78      6994987.48
      1664065.50      6994989.22      1664048.94      6994996.15
      1664007.31      6995032.32      1663984.90      6995038.09
      1663910.97      6995035.83      1663853.40      6994991.71
      1663805.00      6994987.18      1663756.60      6994991.70
      1663711.06      6995029.85      1663686.73      6995037.79
      1663265.50      6995036.78      1663199.43      6994990.47
      1663106.58      6994984.17      1663057.18      6994944.12
      1663002.80      6994931.92      1662957.20      6994894.08
      1662902.82      6994881.88      1662849.07      6994840.24
      1662670.22      6994837.48      1662648.94      6994829.86
      1662599.05      6994790.28      1662463.30      6994784.92
      1662441.26      6994725.05      1662262.76      6994544.21
      1662255.59      6994526.16      1662255.00      6994488.00

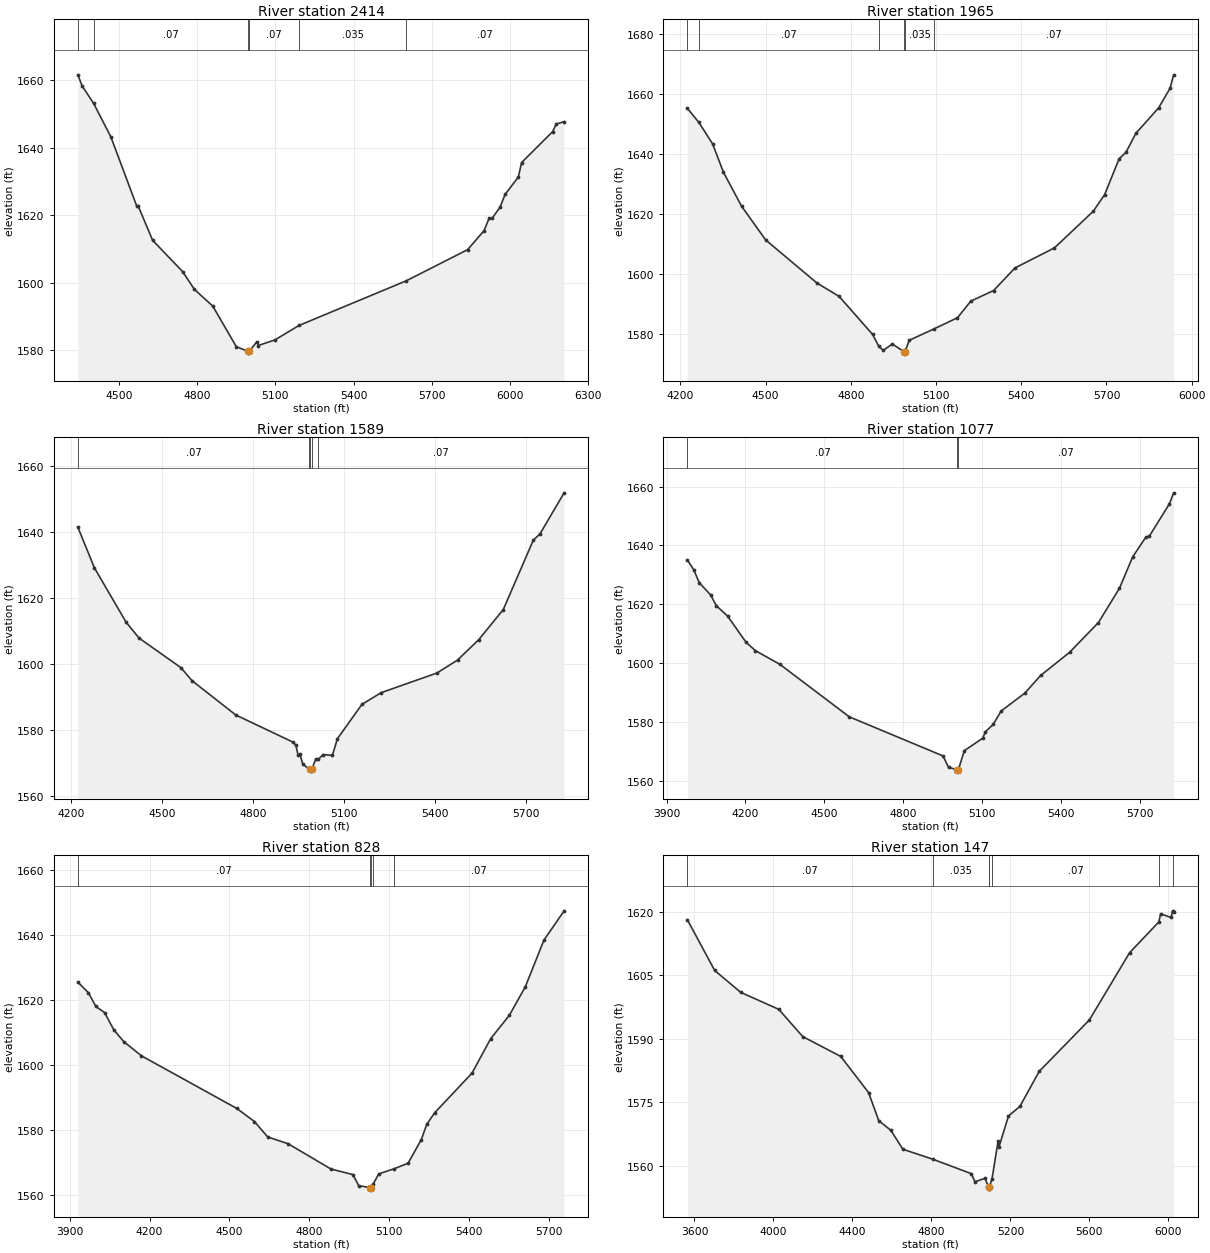
Type RM Length L Ch R = 1,2414,449,449,449
BEGIN DESCRIPTION:
Chimney Creek 1164 5.0
END DESCRIPTION:
XS GIS Cut Line= 3
      1664393.49      6994281.74      1664355.00      6994938.00
      1664175.31      6996131.46
#Sta/Elev= 30
  4343.1 1661.64  4359.4 1658.37  4403.6 1653.17  4469.6 1643.26  4569.1 1622.69
  4574.1 1622.82  4629.8 1612.60  4744.7 1603.33  4790.1 1598.04  4860.2 1593.11
  4950.4 1581.10  4995.9 1579.66  4996.2 1579.16  5000.0 1579.66  5029.9 1582.57
  5035.0 1581.42  5098.9 1583.09  5191.0 1587.36  5602.7 1600.61  5837.4 1609.82
  5900.5 1615.46  5920.7 1619.28  5930.9 1619.07  5961.2 1622.35  5981.4 1626.22
  6032.0 1631.35  6044.4 1635.65  6163.4 1644.81  6177.3 1647.06  6207.4 1647.76
#Mann=6,-1,0
  4343.1    0.16       0  4403.6    0.07       0  4995.9    0.07       0
  5000.0    0.07       0  5191.0   0.035       0  5602.7    0.07       0
Bank Sta=4995.9,5000
Exp/Cntr=0.3,0.1

Type RM Length L Ch R = 1,1965,376,376,376
BEGIN DESCRIPTION:
Mapping XS f4dec8d7
END DESCRIPTION:
XS GIS Cut Line= 3
      1664199.62      6994308.53      1663935.73      6995044.64
      1663696.26      6995943.51
#Sta/Elev= 30
  4224.4 1655.21  4264.8 1650.53  4313.1 1643.38  4351.3 1633.91  4415.1 1622.56
  4500.0 1611.30  4680.6 1596.91  4758.5 1592.46  4876.2 1579.79  4898.4 1575.78
  4914.3 1574.45  4946.2 1576.55  4986.5 1574.01  4986.8 1573.51  4990.7 1574.01
  5005.5 1577.80  5092.4 1581.58  5175.4 1585.33  5222.4 1590.87  5302.7 1594.41
  5377.7 1601.93  5516.9 1608.64  5653.4 1620.85  5693.5 1626.40  5744.6 1638.40
  5768.6 1640.51  5803.5 1646.88  5883.8 1655.39  5923.9 1661.92  5936.6 1666.41
#Mann=6,-1,0
  4224.4    0.16       0  4264.8    0.07       0  4898.4   0.035       0
  4986.5   0.035       0  4990.7   0.035       0  5092.4    0.07       0
Bank Sta=4986.5,4990.7
Exp/Cntr=0.3,0.1

Type RM Length L Ch R = 1,1589,512,512,512
BEGIN DESCRIPTION:
Mapping XS f39fc417
END DESCRIPTION:
XS GIS Cut Line= 3
      1663994.77      6994371.01      1663588.51      6995048.11
      1663487.82      6995857.13
#Sta/Elev= 30
  4222.1 1641.35  4276.9 1629.02  4381.4 1612.55  4424.2 1607.74  4562.2 1598.78
  4599.1 1594.81  4743.4 1584.42  4933.4 1576.14  4941.6 1575.27  4949.0 1572.22
  4954.8 1572.58  4964.5 1569.54  4986.5 1567.93  4989.7 1567.90  4990.0 1567.40
  4993.9 1567.90  5007.3 1571.04  5015.3 1570.95  5031.8 1572.43  5062.0 1572.16
  5078.9 1577.24  5159.7 1587.64  5223.2 1591.19  5407.1 1597.14  5475.2 1601.08
  5545.7 1607.30  5626.3 1616.41  5725.2 1637.41  5747.3 1639.33  5827.0 1651.79
#Mann=5,-1,0
  4222.1    0.07       0  4986.5   0.035       0  4989.7   0.035       0
  4993.9   0.035       0  5015.3    0.07       0
Bank Sta=4989.7,4993.9
Exp/Cntr=0.3,0.1

Type RM Length L Ch R = 1,1077,249,249,249
BEGIN DESCRIPTION:
Mapping XS 1d4cc879
END DESCRIPTION:
XS GIS Cut Line= 3
      1663907.97      6994357.12      1663088.51      6994989.08
      1663112.78      6995803.98
#Sta/Elev= 30
  3979.4 1635.05  4003.7 1631.71  4024.6 1627.30  4068.1 1623.14  4088.9 1619.56
  4132.4 1615.97  4203.0 1607.01  4238.3 1604.21  4331.7 1599.54  4595.3 1581.72
  4952.2 1568.41  4973.0 1564.51  5006.2 1563.75  5006.5 1563.25  5010.5 1563.75
  5033.2 1570.21  5103.2 1574.46  5113.2 1576.62  5143.2 1579.18  5173.2 1583.69
  5263.3 1589.77  5323.3 1595.77  5433.3 1603.62  5543.4 1613.78  5623.4 1625.44
  5673.4 1636.07  5723.5 1642.78  5737.3 1643.19  5813.5 1654.16  5829.5 1657.88
#Mann=3,-1,0
  3979.4    0.07       0  5006.2    0.07       0  5010.5    0.07       0
Bank Sta=5006.2,5010.5
Exp/Cntr=0.3,0.1

Type RM Length L Ch R = 1,828,681,681,681
BEGIN DESCRIPTION:
Mapping XS f013278d
END DESCRIPTION:
XS GIS Cut Line= 3
      1663835.00      6994374.52      1662883.65      6994871.03
      1662855.90      6995623.79
#Sta/Elev= 30
  3930.5 1625.54  3970.2 1622.28  3998.2 1618.05  4030.8 1616.18  4065.9 1610.84
  4102.7 1607.27  4169.0 1602.90  4527.5 1586.71  4593.8 1582.69  4643.6 1577.94
  4720.1 1575.87  4880.9 1568.10  4963.6 1566.37  4985.7 1562.94  5028.5 1562.41
  5028.8 1561.91  5032.8 1562.41  5040.8 1563.63  5060.6 1566.59  5118.1 1568.16
  5170.7 1569.86  5220.7 1577.15  5240.8 1581.80  5270.8 1585.38  5410.9 1597.56
  5480.9 1608.13  5551.0 1615.31  5611.0 1624.07  5681.1 1638.44  5756.9 1647.45
#Mann=5,-1,0
  3930.5    0.07       0  5028.5    0.07       0  5032.8    0.07       0
  5040.8   0.035       0  5118.1    0.07       0
Bank Sta=5028.5,5032.8
Exp/Cntr=0.3,0.1

Type RM Length L Ch R = 1,147,0,0,0
BEGIN DESCRIPTION:
Chimney Creek 1164 1.0
END DESCRIPTION:
XS GIS Cut Line= 3
      1663741.25      6994371.03      1662324.95      6994608.02
      1662512.11      6995617.52
#Sta/Elev= 30
  3564.0 1618.10  3702.2 1606.14  3834.0 1600.97  4026.6 1596.97  4148.3 1590.53
  4340.9 1585.84  4481.3 1577.33  4533.5 1570.67  4594.4 1568.41  4655.2 1563.94
  4807.7 1561.58  5002.5 1558.17  5020.3 1556.26  5071.2 1557.08  5089.4 1555.03
  5089.6 1554.53  5093.7 1555.03  5106.9 1556.97  5137.4 1565.82  5142.4 1564.53
  5190.2 1571.79  5248.1 1574.06  5345.8 1582.32  5600.0 1594.46  5803.4 1610.31
  5951.4 1617.58  5960.7 1619.51  6013.5 1618.64  6021.3 1620.21  6026.7 1619.95
#Mann=7,-1,0
  3564.0    0.07       0  4807.7   0.035       0  5089.4   0.035       0
  5093.7   0.035       0  5106.9    0.07       0  5951.4    0.16       0
  6021.3    0.07       0
Bank Sta=5089.4,5093.7
Exp/Cntr=0.3,0.1

Chan Stop Cuts=-1