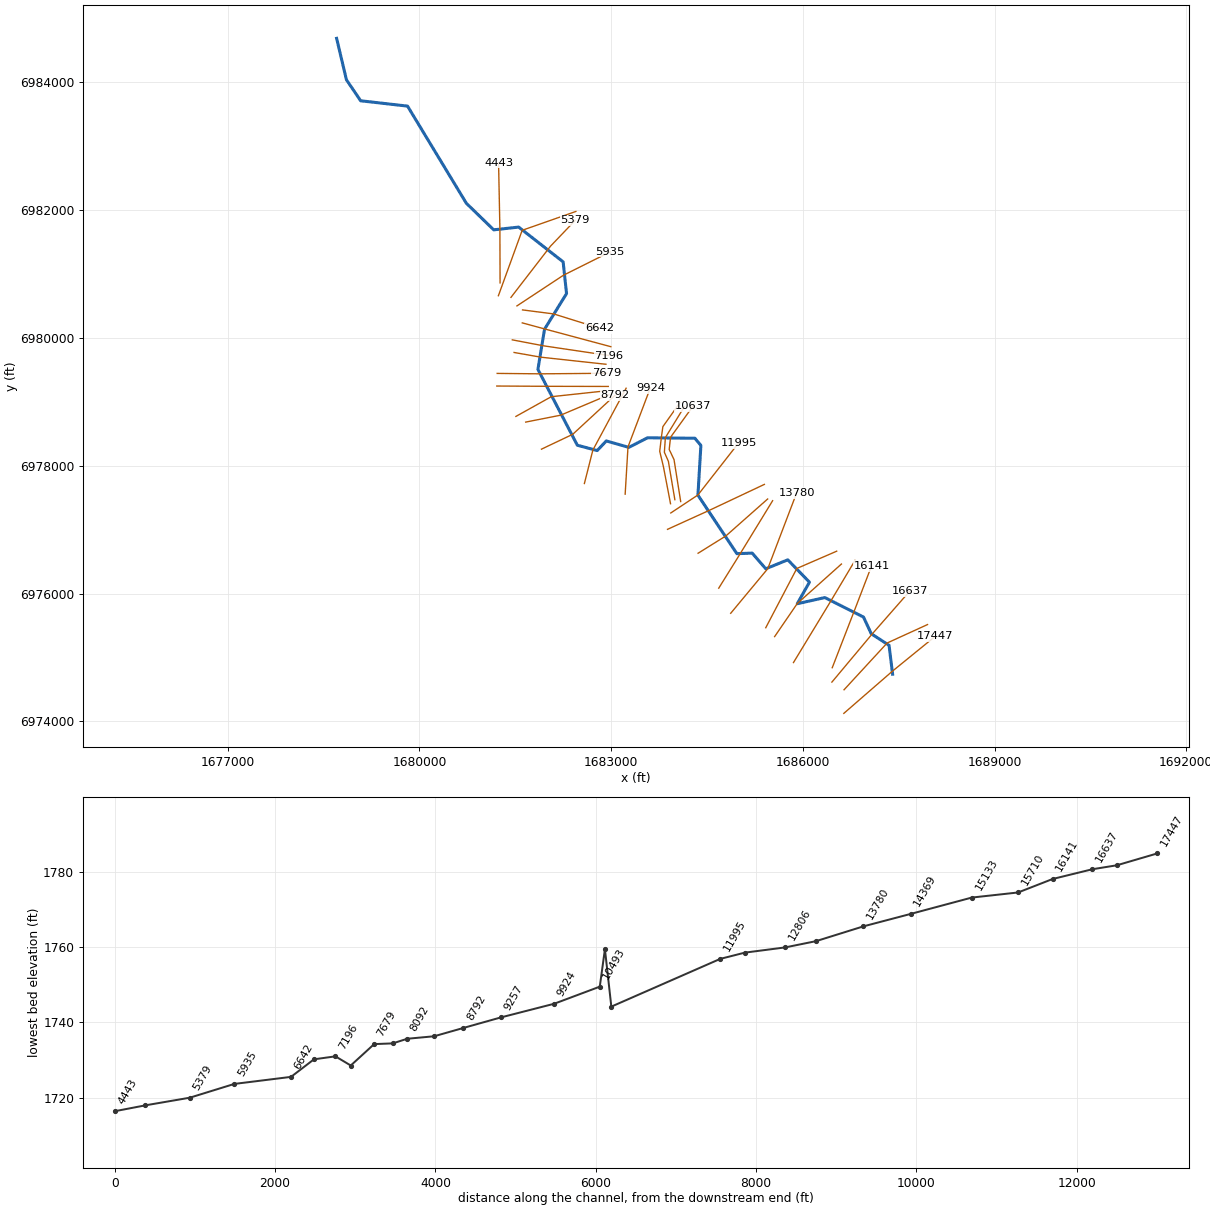
--- Chimney Creek 1166.prj (project) ---

Proj Title=Chimney Creek 1166 Base Level Engineering
Current Plan=p01
Default Exp/Contr=0.3,0.1
English Units
Geom File=g01
Flow File=f01
Plan File=p01
BEGIN DESCRIPTION:
Chimney Creek 1166
END DESCRIPTION:

--- Chimney Creek 1166.p01 (plan) ---

Plan Title=Multiple Run
Short Identifier=Multiple
Geom File=g01
Flow File=f01
Subcritical Flow
K Sum by GR= 0
Std Step Tol= 0.01
Critical Tol= 0.01
Num of Std Step Trials= 20
Max Error Tol= 0.3
Flow Tol Ratio= 0.001
Split Flow NTrial= 30
Split Flow Tol= 0.02
Split Flow Ratio= 0.02
Log Output Level= 0
Friction Slope Method= 1
Unsteady Friction Slope Method= 2
Unsteady Bridges Friction Slope Method= 1
Parabolic Critical Depth
Global Vel Dist=  1 , 1 , 1
Global Log Level= 0
CheckData=True
Encroach Param= -1, 0, 0, 0
BEGIN DESCRIPTION:
Multiple Run
END DESCRIPTION:

--- Chimney Creek 1166.f01 (steady flow) ---

Flow Title=Multiple
Number of Profiles=7
Profile Names=10-year,25-year,50-year,1pct_min,100-year,1pct_plu,500-year
River Rch & RM= Chimney Creek 11,Reach-1,17447
     256     354     435     266     531    1059     802
River Rch & RM= Chimney Creek 11,Reach-1,16141
     285     392     481     294     586    1170     881
River Rch & RM= Chimney Creek 11,Reach-1,12806
     396     555     687     423     844    1685    1291
River Rch & RM= Chimney Creek 11,Reach-1,5935
     510     724     904     561    1120    2235    1741
Boundary for River Rch & Prof#=Chimney Creek 11,Reach-1,1
Up Type=0
Dn Type=3
Dn Slope=0.005
Boundary for River Rch & Prof#=Chimney Creek 11,Reach-1,2
Up Type=0
Dn Type=3
Dn Slope=0.005
Boundary for River Rch & Prof#=Chimney Creek 11,Reach-1,3
Up Type=0
Dn Type=3
Dn Slope=0.005
Boundary for River Rch & Prof#=Chimney Creek 11,Reach-1,4
Up Type=0
Dn Type=3
Dn Slope=0.005
Boundary for River Rch & Prof#=Chimney Creek 11,Reach-1,5
Up Type=0
Dn Type=3
Dn Slope=0.005
Boundary for River Rch & Prof#=Chimney Creek 11,Reach-1,6
Up Type=0
Dn Type=3
Dn Slope=0.005
Boundary for River Rch & Prof#=Chimney Creek 11,Reach-1,7
Up Type=0
Dn Type=3
Dn Slope=0.005

--- Chimney Creek 1166.g01 (geometry) ---

Geom Title=Existing Conditions

River Reach=Chimney Creek 11,Reach-1
Reach XY= 30
      1687405.00      6974738.00      1687349.37      6975190.36
      1687071.30      6975370.87      1686949.38      6975632.38
      1686344.38      6975937.41      1685912.90      6975840.91
      1686103.91      6976178.36      1685764.66      6976527.83
      1685420.22      6976388.24      1685207.67      6976632.70
      1684968.49      6976624.30      1684358.75      6977539.55
      1684405.06      6978318.01      1684311.21      6978430.20
      1683570.21      6978437.49      1683277.85      6978287.70
      1682925.26      6978388.13      1682782.36      6978237.80
      1682471.63      6978321.29      1681855.05      6979508.04
      1681958.55      6980136.53      1682302.94      6980693.86
      1682249.64      6981190.70      1681553.55      6981734.47
      1681163.19      6981691.47      1680734.62      6982107.84
      1679814.81      6983627.49      1679081.47      6983710.86
      1678858.76      6984039.56      1678705.00      6984688.00

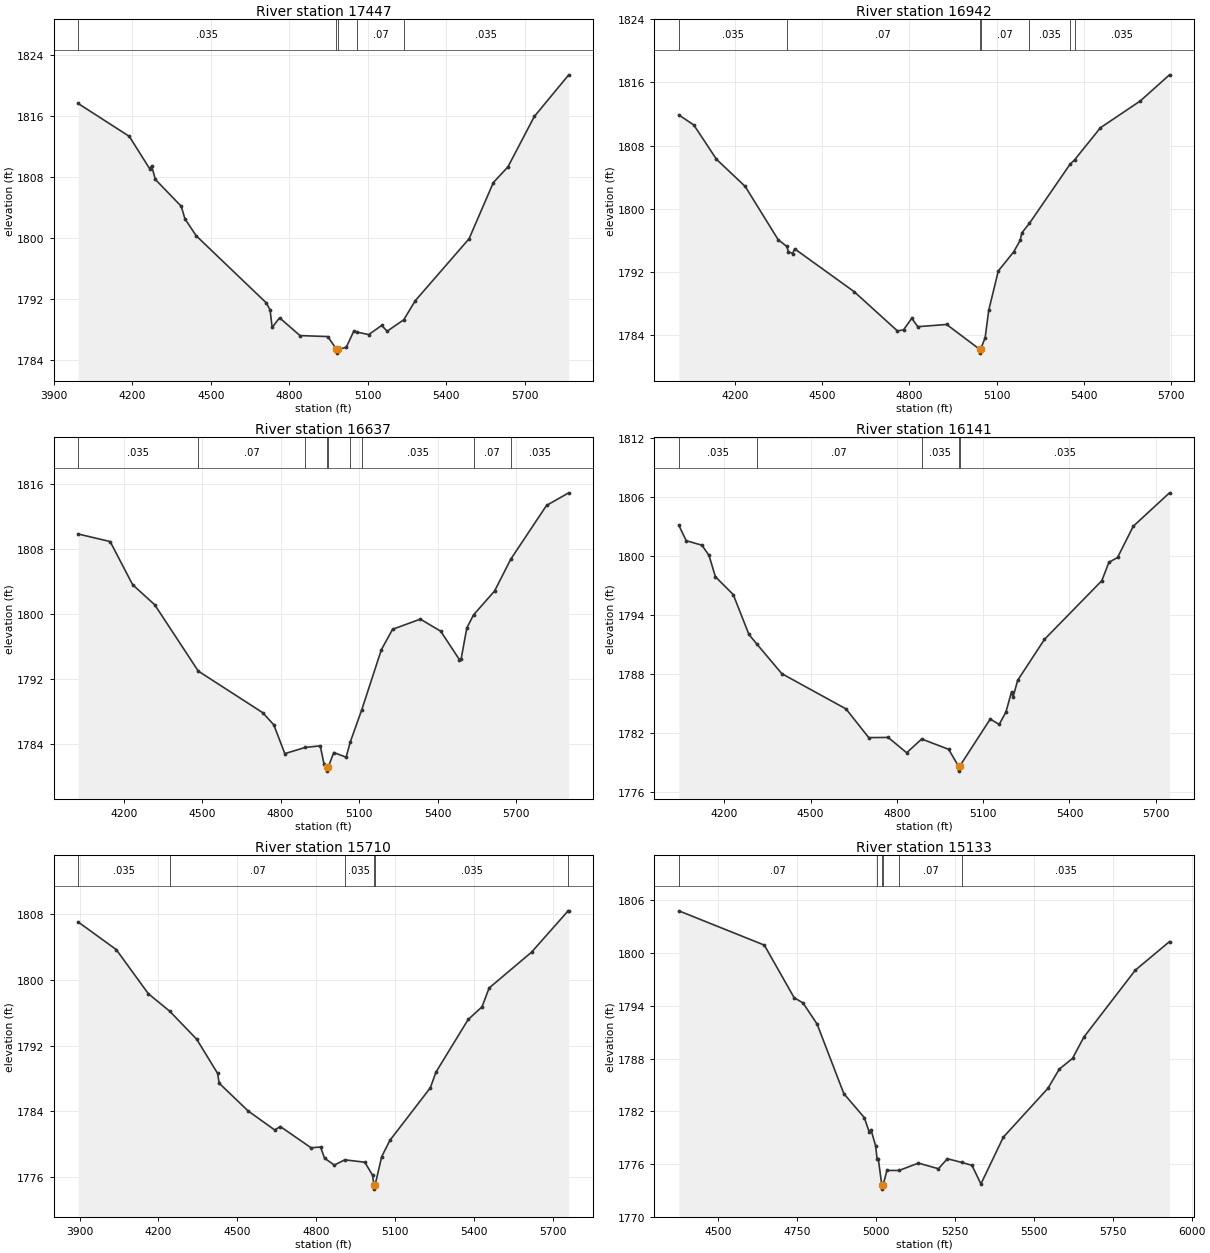
Type RM Length L Ch R = 1,17447,505,505,505
BEGIN DESCRIPTION:
Chimney Creek 1166 34.0
END DESCRIPTION:
XS GIS Cut Line= 3
      1686641.74      6974125.25      1687405.00      6974788.00
      1688075.39      6975333.28
#Sta/Elev= 30
  3993.0 1817.59  4188.6 1813.28  4266.5 1809.04  4274.1 1809.40  4288.3 1807.63
  4387.1 1804.12  4401.3 1802.48  4444.1 1800.26  4712.8 1791.44  4727.0 1790.49
  4734.6 1788.24  4763.1 1789.50  4841.0 1787.17  4947.4 1787.04  4980.5 1785.37
  4980.7 1784.87  4984.5 1785.37  5017.5 1785.61  5046.2 1787.72  5059.9 1787.62
  5103.7 1787.30  5153.2 1788.50  5174.1 1787.74  5237.8 1789.25  5281.1 1791.72
  5487.2 1799.86  5579.9 1807.22  5635.9 1809.29  5736.5 1815.88  5868.0 1821.34
#Mann=5,-1,0
  3993.0   0.035       0  4980.5   0.035       0  4984.5   0.035       0
  5059.9    0.07       0  5237.8   0.035       0
Bank Sta=4980.5,4984.5
Exp/Cntr=0.3,0.1

Type RM Length L Ch R = 1,16942,305,305,305
BEGIN DESCRIPTION:
Mapping XS c6466181
END DESCRIPTION:
XS GIS Cut Line= 3
      1686645.20      6974494.69      1687319.70      6975226.48
      1687951.22      6975514.95
#Sta/Elev= 30
  4006.0 1811.89  4057.7 1810.61  4135.4 1806.28  4234.6 1802.83  4348.1 1796.08
  4377.7 1795.24  4383.2 1794.59  4397.4 1794.33  4404.8 1794.93  4609.5 1789.51
  4758.5 1784.54  4779.6 1784.67  4808.0 1786.13  4828.9 1785.07  4928.2 1785.35
  5041.3 1782.22  5041.5 1781.72  5045.3 1782.22  5060.8 1783.69  5073.0 1787.14
  5106.0 1792.13  5158.4 1794.52  5181.4 1796.00  5186.9 1796.95  5213.3 1798.17
  5352.5 1805.62  5368.4 1806.19  5457.8 1810.27  5594.9 1813.66  5695.5 1816.97
#Mann=7,-1,0
  4006.0   0.035       0  4377.7    0.07       0  5041.3    0.07       0
  5045.3    0.07       0  5213.3   0.035       0  5352.5    0.07       0
  5368.4   0.035       0
Bank Sta=5041.3,5045.3
Exp/Cntr=0.3,0.1

Type RM Length L Ch R = 1,16637,496,496,496
BEGIN DESCRIPTION:
Mapping XS 5972ba7e
END DESCRIPTION:
XS GIS Cut Line= 3
      1686455.15      6974614.53      1687082.72      6975364.50
      1687673.88      6976039.00
#Sta/Elev= 30
  4025.9 1809.83  4148.4 1808.90  4234.3 1803.60  4318.9 1801.12  4485.3 1792.97
  4731.3 1787.86  4773.7 1786.37  4815.9 1782.82  4893.3 1783.58  4951.3 1783.78
  4965.6 1781.55  4977.9 1781.17  4978.1 1780.67  4981.9 1781.17  5002.8 1782.96
  5050.1 1782.38  5065.8 1784.24  5109.5 1788.18  5184.9 1795.61  5227.6 1798.11
  5333.8 1799.36  5411.7 1797.87  5482.8 1794.39  5489.5 1794.45  5511.3 1798.27
  5536.9 1799.88  5617.6 1802.83  5679.0 1806.72  5815.9 1813.34  5900.7 1814.89
#Mann=9,-1,0
  4025.9   0.035       0  4485.3    0.07       0  4893.3   0.035       0
  4977.9   0.035       0  4981.9   0.035       0  5065.8    0.07       0
  5109.5   0.035       0  5536.9    0.07       0  5679.0   0.035       0
Bank Sta=4977.9,4981.9
Exp/Cntr=0.3,0.1

Type RM Length L Ch R = 1,16141,431,431,431
BEGIN DESCRIPTION:
Mapping XS 46f9ad01
END DESCRIPTION:
XS GIS Cut Line= 3
      1686460.53      6974839.50      1686806.90      6975732.77
      1687075.14      6976430.72
#Sta/Elev= 30
  4041.9 1803.09  4067.6 1801.53  4122.1 1801.07  4146.6 1800.04  4169.0 1797.86
  4231.0 1796.05  4285.5 1791.99  4312.3 1791.04  4399.8 1788.00  4623.1 1784.41
  4702.1 1781.49  4769.6 1781.51  4834.0 1779.95  4886.2 1781.35  4979.8 1780.30
  5014.3 1778.58  5014.5 1778.08  5018.3 1778.58  5124.5 1783.38  5155.6 1782.83
  5179.1 1784.10  5198.4 1786.14  5203.8 1785.61  5219.8 1787.32  5313.1 1791.49
  5512.4 1797.46  5537.1 1799.33  5567.1 1799.82  5621.7 1803.00  5747.7 1806.40
#Mann=5,-1,0
  4041.9   0.035       0  4312.3    0.07       0  4886.2   0.035       0
  5014.3   0.035       0  5018.3   0.035       0
Bank Sta=5014.3,5018.3
Exp/Cntr=0.3,0.1

Type RM Length L Ch R = 1,15710,577,577,577
BEGIN DESCRIPTION:
Mapping XS 9485a130
END DESCRIPTION:
XS GIS Cut Line= 3
      1685853.77      6974920.26      1686429.29      6975868.19
      1686817.33      6976519.26
#Sta/Elev= 30
  3894.2 1807.06  4039.4 1803.69  4161.6 1798.31  4243.2 1796.17  4345.7 1792.76
  4425.2 1788.60  4431.0 1787.41  4541.5 1784.02  4642.3 1781.71  4663.7 1782.13
  4780.7 1779.54  4816.7 1779.63  4832.2 1778.27  4869.0 1777.43  4909.2 1778.07
  4985.3 1777.78  5014.6 1776.20  5020.1 1775.00  5020.4 1774.50  5024.3 1775.00
  5049.5 1778.46  5080.6 1780.44  5234.4 1786.84  5255.8 1788.75  5378.5 1795.17
  5431.1 1796.71  5458.3 1799.01  5619.9 1803.38  5758.9 1808.41  5761.1 1808.41
#Mann=6,-1,0
  3894.2   0.035       0  4243.2    0.07       0  4909.2   0.035       0
  5020.1   0.035       0  5024.3   0.035       0  5758.9    0.07       0
Bank Sta=5020.1,5024.3
Exp/Cntr=0.3,0.1

Type RM Length L Ch R = 1,15133,764,764,764
BEGIN DESCRIPTION:
Mapping XS a657c810
END DESCRIPTION:
XS GIS Cut Line= 3
      1685559.06      6975326.73      1685913.23      6975844.10
      1686604.17      6976462.13
#Sta/Elev= 30
  4375.8 1804.81  4646.5 1800.91  4740.9 1794.93  4769.1 1794.33  4813.6 1791.93
  4898.4 1784.01  4963.4 1781.28  4978.3 1779.68  4984.3 1779.93  4999.3 1778.03
  5003.5 1776.63  5007.3 1776.63  5018.5 1773.65  5018.8 1773.15  5022.9 1773.65
  5034.9 1775.28  5072.9 1775.27  5134.4 1776.11  5197.9 1775.47  5226.3 1776.61
  5272.4 1776.18  5304.1 1775.86  5332.5 1773.74  5403.5 1779.06  5544.8 1784.62
  5580.7 1786.80  5622.6 1788.02  5658.5 1790.44  5821.5 1798.06  5929.8 1801.31
#Mann=6,-1,0
  4375.8    0.07       0  5003.5   0.035       0  5018.5    0.07       0
  5022.9   0.035       0  5072.9    0.07       0  5272.4   0.035       0
Bank Sta=5018.5,5022.9
Exp/Cntr=0.3,0.1

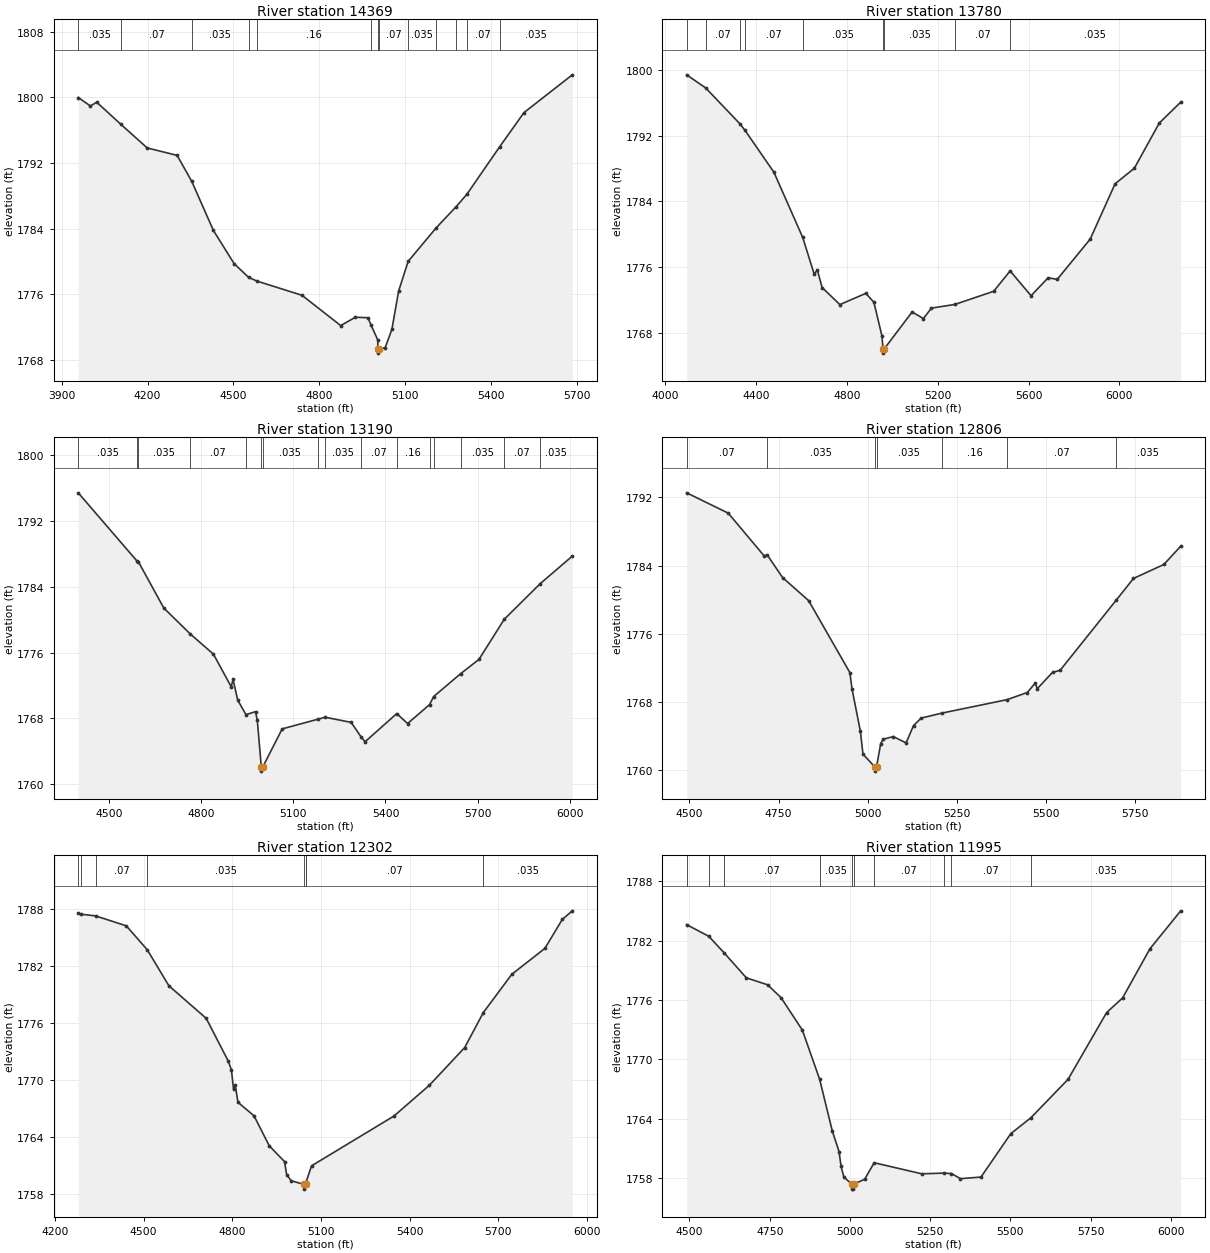
Type RM Length L Ch R = 1,14369,589,589,589
BEGIN DESCRIPTION:
Mapping XS ebbfc96d
END DESCRIPTION:
XS GIS Cut Line= 3
      1685420.16      6975465.60      1685906.29      6976392.71
      1686530.01      6976662.99
#Sta/Elev= 30
  3957.6 1799.99  4000.1 1798.96  4022.1 1799.42  4107.2 1796.70  4198.6 1793.84
  4303.2 1792.93  4354.2 1789.76  4430.0 1783.77  4502.3 1779.72  4553.2 1778.04
  4582.3 1777.59  4739.4 1775.86  4874.9 1772.16  4926.0 1773.18  4970.1 1773.12
  4980.9 1772.22  5004.4 1770.41  5004.6 1769.30  5004.9 1768.80  5009.0 1769.30
  5030.3 1769.48  5053.8 1771.71  5077.2 1776.37  5110.6 1780.00  5208.8 1784.10
  5278.7 1786.69  5315.5 1788.17  5430.5 1793.99  5515.3 1798.15  5684.2 1802.76
#Mann=13,-1,0
  3957.6   0.035       0  4107.2    0.07       0  4354.2   0.035       0
  4553.2    0.07       0  4582.3    0.16       0  4980.9    0.07       0
  5004.6    0.07       0  5009.0    0.07       0  5110.6   0.035       0
  5208.8    0.07       0  5278.7   0.035       0  5315.5    0.07       0
  5430.5   0.035       0
Bank Sta=5004.6,5009
Exp/Cntr=0.3,0.1

Type RM Length L Ch R = 1,13780,590,590,590
BEGIN DESCRIPTION:
Mapping XS 97ec6c7d
END DESCRIPTION:
XS GIS Cut Line= 3
      1684871.58      6975691.34      1685451.43      6976389.24
      1685902.78      6977573.17
#Sta/Elev= 30
  4095.3 1799.39  4179.3 1797.79  4329.2 1793.44  4350.5 1792.69  4479.3 1787.53
  4605.9 1779.60  4656.3 1775.15  4670.7 1775.59  4691.5 1773.49  4769.6 1771.41
  4884.0 1772.78  4919.4 1771.69  4954.5 1767.63  4959.8 1766.00  4960.1 1765.50
  4964.3 1766.00  5087.6 1770.51  5137.1 1769.71  5172.6 1770.98  5275.7 1771.43
  5446.6 1773.03  5518.9 1775.51  5611.1 1772.49  5686.3 1774.68  5726.1 1774.48
  5871.2 1779.38  5980.9 1786.12  6065.8 1788.02  6175.4 1793.52  6269.7 1796.06
#Mann=9,-1,0
  4095.3   0.035       0  4179.3    0.07       0  4329.2   0.035       0
  4350.5    0.07       0  4605.9   0.035       0  4959.8   0.035       0
  4964.3   0.035       0  5275.7    0.07       0  5518.9   0.035       0
Bank Sta=4959.8,4964.3
Exp/Cntr=0.3,0.1

Type RM Length L Ch R = 1,13190,384,384,384
BEGIN DESCRIPTION:
Mapping XS 30fe9cfd
END DESCRIPTION:
XS GIS Cut Line= 3
      1684684.42      6976084.21      1685002.12      6976594.62
      1685527.85      6977453.48
#Sta/Elev= 30
  4400.0 1795.44  4590.1 1787.19  4595.6 1787.07  4678.4 1781.43  4764.6 1778.27
  4840.1 1775.81  4897.9 1771.84  4903.8 1772.75  4919.2 1770.21  4946.0 1768.45
  4977.0 1768.82  4982.9 1767.74  4995.9 1762.08  4996.2 1761.58  5000.6 1762.08
  5063.8 1766.72  5180.7 1767.90  5203.5 1768.14  5288.4 1767.51  5320.2 1765.77
  5333.5 1765.15  5436.8 1768.58  5472.1 1767.37  5543.7 1769.68  5556.8 1770.65
  5644.8 1773.44  5704.3 1775.17  5786.8 1780.06  5903.5 1784.38  6008.2 1787.74
#Mann=16,-1,0
  4400.0   0.035       0  4590.1    0.07       0  4595.6   0.035       0
  4764.6    0.07       0  4946.0   0.035       0  4995.9   0.035       0
  5000.6   0.035       0  5180.7    0.07       0  5203.5   0.035       0
  5320.2    0.07       0  5436.8    0.16       0  5543.7   0.035       0
  5556.8    0.07       0  5644.8   0.035       0  5786.8    0.07       0
  5903.5   0.035       0
Bank Sta=4995.9,5000.6
Exp/Cntr=0.3,0.1

Type RM Length L Ch R = 1,12806,504,504,504
BEGIN DESCRIPTION:
Mapping XS 017b511c
END DESCRIPTION:
XS GIS Cut Line= 3
      1684361.52      6976631.09      1684796.39      6976901.91
      1685450.01      6977480.01
#Sta/Elev= 30
  4492.1 1792.52  4608.7 1790.14  4709.0 1785.15  4718.1 1785.24  4760.9 1782.60
  4834.1 1779.89  4949.7 1771.46  4955.6 1769.55  4979.2 1764.57  4986.3 1761.92
  5019.3 1760.42  5019.7 1759.92  5024.4 1760.42  5036.1 1763.15  5042.8 1763.65
  5071.2 1763.97  5107.2 1763.23  5128.1 1765.26  5149.4 1766.13  5207.9 1766.72
  5391.0 1768.30  5446.8 1769.13  5468.6 1770.20  5475.2 1769.59  5517.9 1771.50
  5538.8 1771.72  5695.7 1779.92  5744.6 1782.49  5829.9 1784.13  5877.0 1786.27
#Mann=7,-1,0
  4492.1    0.07       0  4718.1   0.035       0  5019.3   0.035       0
  5024.4   0.035       0  5207.9    0.16       0  5391.0    0.07       0
  5695.7   0.035       0
Bank Sta=5019.3,5024.4
Exp/Cntr=0.3,0.1

Type RM Length L Ch R = 1,12302,307,307,307
BEGIN DESCRIPTION:
Mapping XS fe772787
END DESCRIPTION:
XS GIS Cut Line= 3
      1683883.16      6977005.19      1684536.85      6977302.09
      1685398.86      6977708.35
#Sta/Elev= 30
  4279.0 1787.55  4289.5 1787.43  4337.4 1787.26  4441.6 1786.21  4512.3 1783.70
  4585.6 1779.91  4711.9 1776.48  4786.6 1771.98  4797.2 1771.04  4804.2 1769.02
  4809.7 1769.51  4819.2 1767.66  4873.4 1766.24  4925.1 1763.08  4976.7 1761.42
  4983.9 1760.04  4999.8 1759.40  5042.7 1759.03  5043.1 1758.53  5047.9 1759.03
  5049.8 1759.30  5068.1 1760.98  5347.0 1766.22  5466.5 1769.45  5585.9 1773.41
  5649.1 1777.10  5745.4 1781.12  5857.2 1783.84  5915.9 1786.88  5949.9 1787.79
#Mann=8,-1,0
  4279.0    0.07       0  4289.5   0.035       0  4337.4    0.07       0
  4512.3   0.035       0  5042.7   0.035       0  5047.9   0.035       0
  5049.8    0.07       0  5649.1   0.035       0
Bank Sta=5042.7,5047.9
Exp/Cntr=0.3,0.1

Type RM Length L Ch R = 1,11995,1358,1358,1358
BEGIN DESCRIPTION:
Mapping XS 89c3610d
END DESCRIPTION:
XS GIS Cut Line= 3
      1683933.75      6977260.96      1684358.20      6977542.19
      1684992.98      6978353.88
#Sta/Elev= 30
  4491.2 1783.62  4560.0 1782.45  4608.0 1780.77  4677.3 1778.24  4743.5 1777.54
  4785.6 1776.23  4851.8 1772.95  4905.6 1767.98  4945.0 1762.76  4966.1 1760.66
  4972.5 1759.16  4981.1 1758.09  5006.0 1757.37  5006.5 1756.87  5010.9 1756.87
  5011.3 1757.37  5045.7 1757.86  5075.6 1759.54  5223.6 1758.42  5292.2 1758.49
  5316.5 1758.45  5344.2 1757.93  5408.4 1758.09  5501.5 1762.49  5563.7 1764.08
  5679.6 1767.97  5799.9 1774.73  5849.7 1776.21  5934.7 1781.17  6030.8 1785.02
#Mann=10,-1,0
  4491.2    0.07       0  4560.0   0.035       0  4608.0    0.07       0
  4905.6   0.035       0  5006.0   0.035       0  5011.3   0.035       0
  5075.6    0.07       0  5292.2   0.035       0  5316.5    0.07       0
  5563.7   0.035       0
Bank Sta=5006,5011.3
Exp/Cntr=0.3,0.1

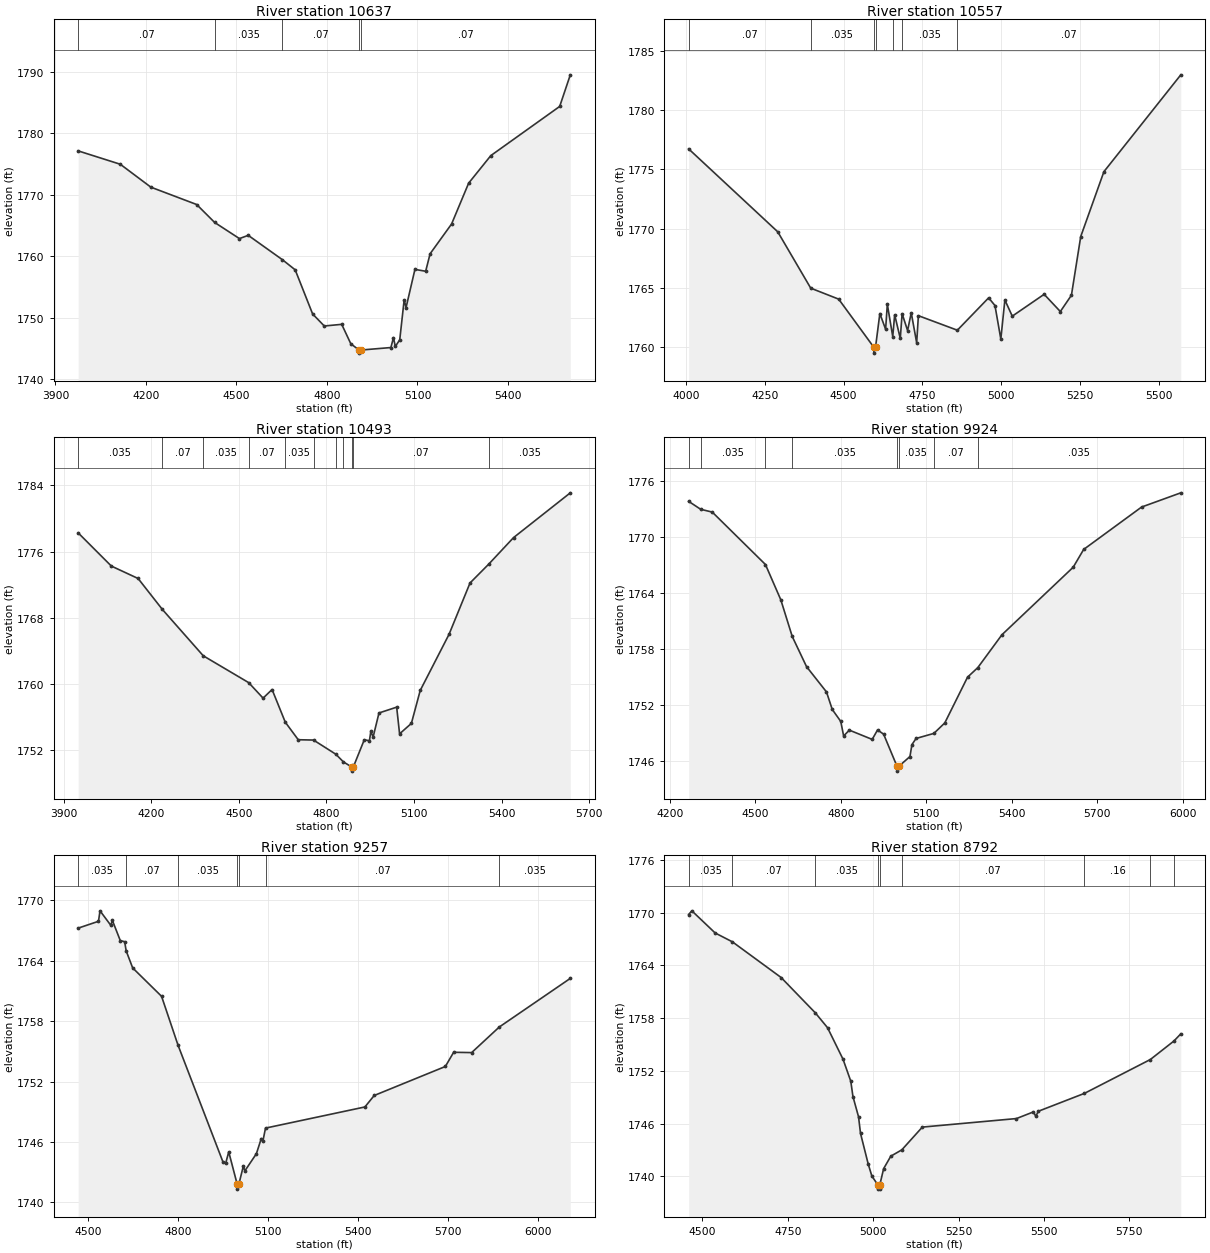
Type RM Length L Ch R = 1,10637,80,80,80
BEGIN DESCRIPTION:
Mapping XS 5c5f07a2
END DESCRIPTION:
XS GIS Cut Line= 5
      1684088.94      6977440.07      1683984.76      6978096.36
      1683909.24      6978255.21      1683930.07      6978445.32
      1684280.84      6978931.19
#Sta/Elev= 30
  3975.5 1777.15  4115.2 1774.97  4216.4 1771.24  4368.3 1768.41  4427.8 1765.49
  4510.0 1762.86  4539.1 1763.39  4651.8 1759.44  4694.7 1757.77  4752.5 1750.58
  4791.1 1748.62  4848.9 1748.89  4879.1 1745.72  4906.5 1744.70  4906.9 1744.20
  4912.0 1744.70  5011.9 1745.11  5020.4 1746.73  5026.5 1745.28  5041.2 1746.37
  5055.9 1752.90  5062.1 1751.62  5091.5 1757.84  5127.1 1757.54  5141.8 1760.39
  5213.0 1765.24  5269.5 1771.89  5343.0 1776.38  5571.2 1784.39  5606.4 1789.54
#Mann=5,-1,0
  3975.5    0.07       0  4427.8   0.035       0  4651.8    0.07       0
  4906.5    0.07       0  4912.0    0.07       0
Bank Sta=4906.5,4912
Exp/Cntr=0.3,0.1

Type RM Length L Ch R = 1,10557,64,64,64
BEGIN DESCRIPTION:
Mapping XS 4f92c4c2
END DESCRIPTION:
XS GIS Cut Line= 5
      1683997.78      6977468.76      1683896.22      6978070.32
      1683833.72      6978210.94      1683849.35      6978440.11
      1684145.77      6978923.74
#Sta/Elev= 30
  4008.4 1776.74  4291.0 1769.72  4395.6 1764.95  4484.3 1764.02  4595.6 1759.95
  4596.0 1759.45  4601.1 1759.95  4614.8 1762.80  4633.1 1761.47  4638.5 1763.59
  4655.7 1760.85  4661.8 1762.70  4679.6 1760.69  4685.4 1762.79  4702.8 1761.36
  4714.4 1762.87  4731.6 1760.32  4737.0 1762.62  4860.6 1761.39  4959.8 1764.13
  4979.9 1763.48  4998.5 1760.64  5011.3 1763.95  5034.8 1762.58  5135.9 1764.43
  5187.2 1762.97  5222.4 1764.35  5251.9 1769.32  5325.4 1774.81  5569.3 1783.01
#Mann=7,-1,0
  4008.4    0.07       0  4395.6   0.035       0  4595.6    0.07       0
  4601.1   0.035       0  4655.7    0.07       0  4685.4   0.035       0
  4860.6    0.07       0
Bank Sta=4595.6,4601.1
Exp/Cntr=0.3,0.1

Type RM Length L Ch R = 1,10493,569,569,569
BEGIN DESCRIPTION:
Mapping XS cf058e2f
END DESCRIPTION:
XS GIS Cut Line= 6
      1683930.07      6977406.29      1683818.10      6977989.59
      1683760.80      6978226.57      1683786.85      6978445.32
      1683810.28      6978611.98      1684075.91      6978986.99
#Sta/Elev= 30
  3949.3 1778.26  4063.0 1774.25  4154.7 1772.75  4237.9 1769.01  4377.9 1763.42
  4533.5 1760.18  4582.8 1758.31  4613.6 1759.35  4658.8 1755.41  4703.2 1753.29
  4755.6 1753.25  4832.0 1751.54  4858.1 1750.61  4886.4 1750.00  4886.9 1749.50
  4891.9 1750.00  4929.5 1753.29  4947.0 1753.16  4952.0 1754.31  4959.7 1753.61
  4979.8 1756.52  5040.4 1757.22  5050.4 1754.00  5090.8 1755.26  5121.1 1759.24
  5219.8 1766.01  5291.7 1772.21  5355.7 1774.48  5440.6 1777.68  5635.2 1783.09
#Mann=11,-1,0
  3949.3   0.035       0  4237.9    0.07       0  4377.9   0.035       0
  4533.5    0.07       0  4658.8   0.035       0  4755.6    0.07       0
  4832.0   0.035       0  4858.1    0.07       0  4886.4    0.07       0
  4891.9    0.07       0  5355.7   0.035       0
Bank Sta=4886.4,4891.9
Exp/Cntr=0.3,0.1

Type RM Length L Ch R = 1,9924,667,667,667
BEGIN DESCRIPTION:
Mapping XS 57597e9d
END DESCRIPTION:
XS GIS Cut Line= 3
      1683220.18      6977555.25      1683264.45      6978294.80
      1683613.42      6979216.69
#Sta/Elev= 30
  4266.4 1773.79  4308.6 1772.94  4349.3 1772.64  4535.8 1767.04  4589.7 1763.27
  4629.8 1759.35  4679.9 1756.13  4750.0 1753.42  4770.2 1751.55  4800.1 1750.27
  4810.1 1748.72  4830.2 1749.34  4910.3 1748.35  4929.1 1749.36  4950.4 1748.91
  4997.6 1745.46  4998.1 1744.96  5003.3 1745.46  5042.8 1746.52  5049.7 1747.79
  5064.2 1748.45  5126.6 1748.99  5165.0 1750.11  5244.8 1755.00  5280.8 1756.02
  5365.4 1759.53  5615.5 1766.75  5652.2 1768.65  5855.4 1773.18  5993.0 1774.70
#Mann=8,-1,0
  4266.4    0.07       0  4308.6   0.035       0  4535.8    0.07       0
  4629.8   0.035       0  4997.6   0.035       0  5003.3   0.035       0
  5126.6    0.07       0  5280.8   0.035       0
Bank Sta=4997.6,5003.3
Exp/Cntr=0.3,0.1

Type RM Length L Ch R = 1,9257,465,465,465
BEGIN DESCRIPTION:
Mapping XS 8f2e2744
END DESCRIPTION:
XS GIS Cut Line= 3
      1682582.15      6977722.12      1682714.97      6978245.58
      1683235.08      6979212.98
#Sta/Elev= 30
  4467.9 1767.24  4535.6 1767.92  4540.7 1768.96  4576.6 1767.52  4581.7 1768.02
  4608.1 1766.01  4622.7 1765.89  4627.8 1764.98  4649.4 1763.29  4745.6 1760.47
  4800.6 1755.60  4950.4 1743.99  4958.9 1743.87  4969.2 1745.02  4997.2 1741.82
  4997.7 1741.32  5003.0 1741.82  5017.5 1743.57  5023.1 1743.14  5061.3 1744.84
  5077.5 1746.34  5083.2 1746.13  5091.6 1747.38  5422.5 1749.48  5453.5 1750.62
  5690.3 1753.50  5717.9 1754.91  5777.9 1754.88  5869.8 1757.42  6106.3 1762.25
#Mann=7,-1,0
  4467.9   0.035       0  4627.8    0.07       0  4800.6   0.035       0
  4997.2   0.035       0  5003.0   0.035       0  5091.6    0.07       0
  5869.8   0.035       0
Bank Sta=4997.2,5003
Exp/Cntr=0.3,0.1

Type RM Length L Ch R = 1,8792,365,365,365
BEGIN DESCRIPTION:
Mapping XS 732bc861
END DESCRIPTION:
XS GIS Cut Line= 3
      1681910.35      6978259.50      1682399.95      6978492.15
      1683060.60      6979102.51
#Sta/Elev= 30
  4459.6 1769.79  4469.0 1770.21  4537.2 1767.69  4587.8 1766.68  4730.5 1762.62
  4830.4 1758.61  4866.4 1756.91  4911.8 1753.32  4934.5 1750.82  4940.8 1749.08
  4957.2 1746.77  4963.0 1744.88  4985.5 1741.40  4996.2 1740.03  5013.4 1739.04
  5013.9 1738.54  5019.1 1738.54  5019.6 1739.04  5030.7 1740.87  5051.7 1742.29
  5084.0 1743.01  5144.1 1745.60  5419.7 1746.57  5469.5 1747.33  5476.4 1746.82
  5483.7 1747.40  5619.0 1749.44  5811.9 1753.29  5880.8 1755.39  5901.1 1756.21
#Mann=9,-1,0
  4459.6   0.035       0  4587.8    0.07       0  4830.4   0.035       0
  5013.4   0.035       0  5019.6   0.035       0  5084.0    0.07       0
  5619.0    0.16       0  5811.9    0.07       0  5880.8   0.035       0
Bank Sta=5013.4,5019.6
Exp/Cntr=0.3,0.1

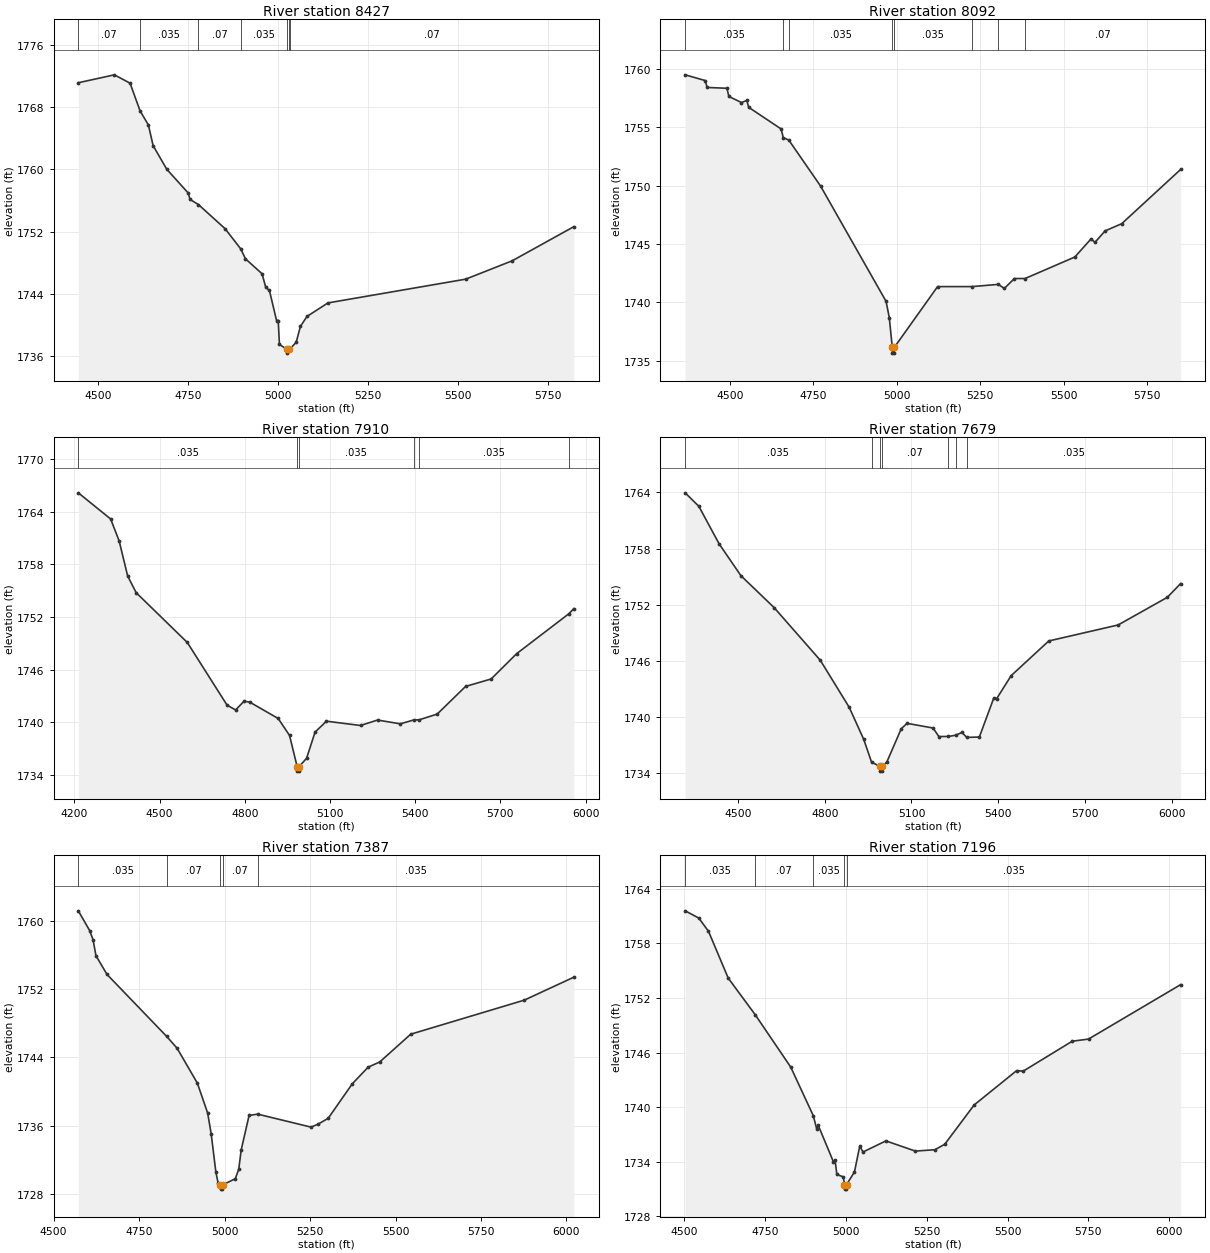
Type RM Length L Ch R = 1,8427,335,335,335
BEGIN DESCRIPTION:
Mapping XS 0e730aa2
END DESCRIPTION:
XS GIS Cut Line= 3
      1681663.84      6978683.12      1682208.98      6978790.76
      1682965.97      6979110.22
#Sta/Elev= 30
  4444.5 1771.17  4544.8 1772.19  4588.4 1771.11  4616.2 1767.54  4639.3 1765.73
  4652.5 1763.06  4690.3 1760.03  4750.0 1756.96  4755.1 1756.13  4778.3 1755.48
  4852.6 1752.36  4896.2 1749.75  4909.0 1748.49  4955.2 1746.56  4965.5 1744.82
  4975.7 1744.41  4995.6 1740.53  5000.2 1740.53  5003.6 1737.45  5024.2 1736.83
  5024.7 1736.33  5030.5 1736.83  5032.2 1736.85  5050.1 1737.72  5061.9 1739.77
  5080.2 1741.06  5138.4 1742.80  5521.3 1745.86  5650.7 1748.23  5821.8 1752.62
#Mann=7,-1,0
  4444.5    0.07       0  4616.2   0.035       0  4778.3    0.07       0
  4896.2   0.035       0  5024.2   0.035       0  5030.5   0.035       0
  5032.2    0.07       0
Bank Sta=5024.2,5030.5
Exp/Cntr=0.3,0.1

Type RM Length L Ch R = 1,8092,182,182,182
BEGIN DESCRIPTION:
Mapping XS 28293ace
END DESCRIPTION:
XS GIS Cut Line= 3
      1681510.63      6978772.08      1682064.04      6979080.26
      1682910.21      6979171.38
#Sta/Elev= 30
  4365.9 1759.47  4425.9 1758.98  4431.7 1758.39  4491.1 1758.32  4496.8 1757.62
  4534.6 1757.10  4550.6 1757.28  4556.3 1756.69  4653.4 1754.84  4659.8 1754.10
  4676.4 1753.89  4771.5 1749.96  4967.8 1740.10  4977.5 1738.70  4986.4 1736.17
  4986.9 1735.67  4992.2 1735.67  4992.7 1736.17  5122.2 1741.36  5226.1 1741.36
  5304.1 1741.55  5322.1 1741.20  5352.3 1742.05  5384.3 1742.05  5533.4 1743.89
  5582.0 1745.44  5593.7 1745.14  5623.9 1746.12  5673.9 1746.74  5850.4 1751.38
#Mann=8,-1,0
  4365.9   0.035       0  4659.8    0.07       0  4676.4   0.035       0
  4986.4   0.035       0  4992.7   0.035       0  5226.1    0.07       0
  5304.1   0.035       0  5384.3    0.07       0
Bank Sta=4986.4,4992.7
Exp/Cntr=0.3,0.1

Type RM Length L Ch R = 1,7910,231,231,231
BEGIN DESCRIPTION:
Mapping XS 7297a43c
END DESCRIPTION:
XS GIS Cut Line= 3
      1681211.19      6979247.36      1681996.77      6979243.02
      1682955.97      6979240.85
#Sta/Elev= 30
  4213.7 1766.15  4327.5 1763.17  4357.5 1760.67  4387.5 1756.67  4417.5 1754.77
  4597.5 1749.10  4737.5 1741.96  4767.5 1741.41  4797.5 1742.41  4817.5 1742.30
  4917.5 1740.44  4957.5 1738.51  4984.4 1734.94  4984.9 1734.44  4990.2 1734.44
  4990.7 1734.94  5017.5 1735.90  5047.5 1738.89  5087.5 1740.13  5207.5 1739.64
  5267.5 1740.26  5347.5 1739.83  5395.2 1740.27  5414.4 1740.29  5477.5 1740.94
  5577.5 1744.09  5667.5 1744.94  5757.5 1747.83  5940.7 1752.36  5958.5 1752.95
#Mann=6,-1,0
  4213.7   0.035       0  4984.4   0.035       0  4990.7   0.035       0
  5395.2    0.07       0  5414.4   0.035       0  5940.7    0.07       0
Bank Sta=4984.4,4990.7
Exp/Cntr=0.3,0.1

Type RM Length L Ch R = 1,7679,292,292,292
BEGIN DESCRIPTION:
Mapping XS 4d846f87
END DESCRIPTION:
XS GIS Cut Line= 3
      1681217.70      6979444.84      1681901.28      6979438.33
      1682931.04      6979447.00
#Sta/Elev= 30
  4317.5 1763.95  4364.8 1762.51  4434.8 1758.51  4510.2 1755.11  4624.8 1751.71
  4784.8 1746.08  4884.8 1741.06  4934.8 1737.65  4962.1 1735.20  4991.6 1734.75
  4992.1 1734.25  4997.6 1734.25  4998.1 1734.75  5014.8 1735.22  5064.8 1738.78
  5084.8 1739.35  5174.8 1738.85  5194.8 1737.94  5227.8 1737.95  5252.4 1738.08
  5274.8 1738.38  5291.0 1737.85  5334.8 1737.89  5384.8 1742.06  5394.8 1741.99
  5444.8 1744.44  5574.8 1748.14  5814.9 1749.85  5984.9 1752.80  6030.9 1754.27
#Mann=7,-1,0
  4317.5   0.035       0  4962.1    0.07       0  4991.6    0.07       0
  4998.1    0.07       0  5227.8   0.035       0  5252.4    0.07       0
  5291.0   0.035       0
Bank Sta=4991.6,4998.1
Exp/Cntr=0.3,0.1

Type RM Length L Ch R = 1,7387,191,191,191
BEGIN DESCRIPTION:
Mapping XS a6409bbb
END DESCRIPTION:
XS GIS Cut Line= 3
      1681482.43      6979772.53      1681901.28      6979698.75
      1682919.08      6979588.07
#Sta/Elev= 30
  4572.2 1761.19  4605.3 1758.88  4615.4 1757.79  4623.8 1755.93  4656.0 1753.74
  4830.9 1746.46  4861.0 1745.09  4920.2 1741.01  4950.5 1737.49  4960.7 1735.08
  4974.4 1730.60  4981.0 1729.29  4987.9 1729.07  4988.4 1728.57  4993.9 1728.57
  4994.4 1729.07  5031.4 1729.79  5041.5 1730.92  5048.6 1733.17  5071.7 1737.21
  5096.7 1737.36  5252.7 1735.84  5272.8 1736.17  5303.0 1736.87  5373.4 1740.91
  5419.7 1742.86  5453.9 1743.48  5544.4 1746.73  5876.4 1750.72  6021.3 1753.41
#Mann=5,-1,0
  4572.2   0.035       0  4830.9    0.07       0  4987.9    0.07       0
  4994.4    0.07       0  5096.7   0.035       0
Bank Sta=4987.9,4994.4
Exp/Cntr=0.3,0.1

Type RM Length L Ch R = 1,7196,268,268,268
BEGIN DESCRIPTION:
Mapping XS 5eee8a69
END DESCRIPTION:
XS GIS Cut Line= 3
      1681454.27      6979970.01      1681942.52      6979876.70
      1682966.83      6979724.79
#Sta/Elev= 30
  4502.7 1761.58  4544.6 1760.79  4574.7 1759.34  4635.8 1754.19  4719.2 1750.17
  4829.2 1744.41  4899.1 1739.06  4909.3 1737.65  4914.4 1738.00  4961.4 1733.99
  4966.4 1734.20  4971.8 1732.61  4992.1 1732.34  4995.3 1731.50  4995.8 1731.00
  5001.3 1731.00  5001.8 1731.50  5026.3 1732.88  5042.7 1735.73  5052.8 1735.08
  5123.6 1736.30  5214.6 1735.18  5275.3 1735.33  5305.6 1735.93  5396.6 1740.25
  5528.0 1744.02  5548.2 1743.96  5699.8 1747.25  5750.4 1747.49  6035.3 1753.47
#Mann=5,-1,0
  4502.7   0.035       0  4719.2    0.07       0  4899.1   0.035       0
  4995.3   0.035       0  5001.8   0.035       0
Bank Sta=4995.3,5001.8
Exp/Cntr=0.3,0.1

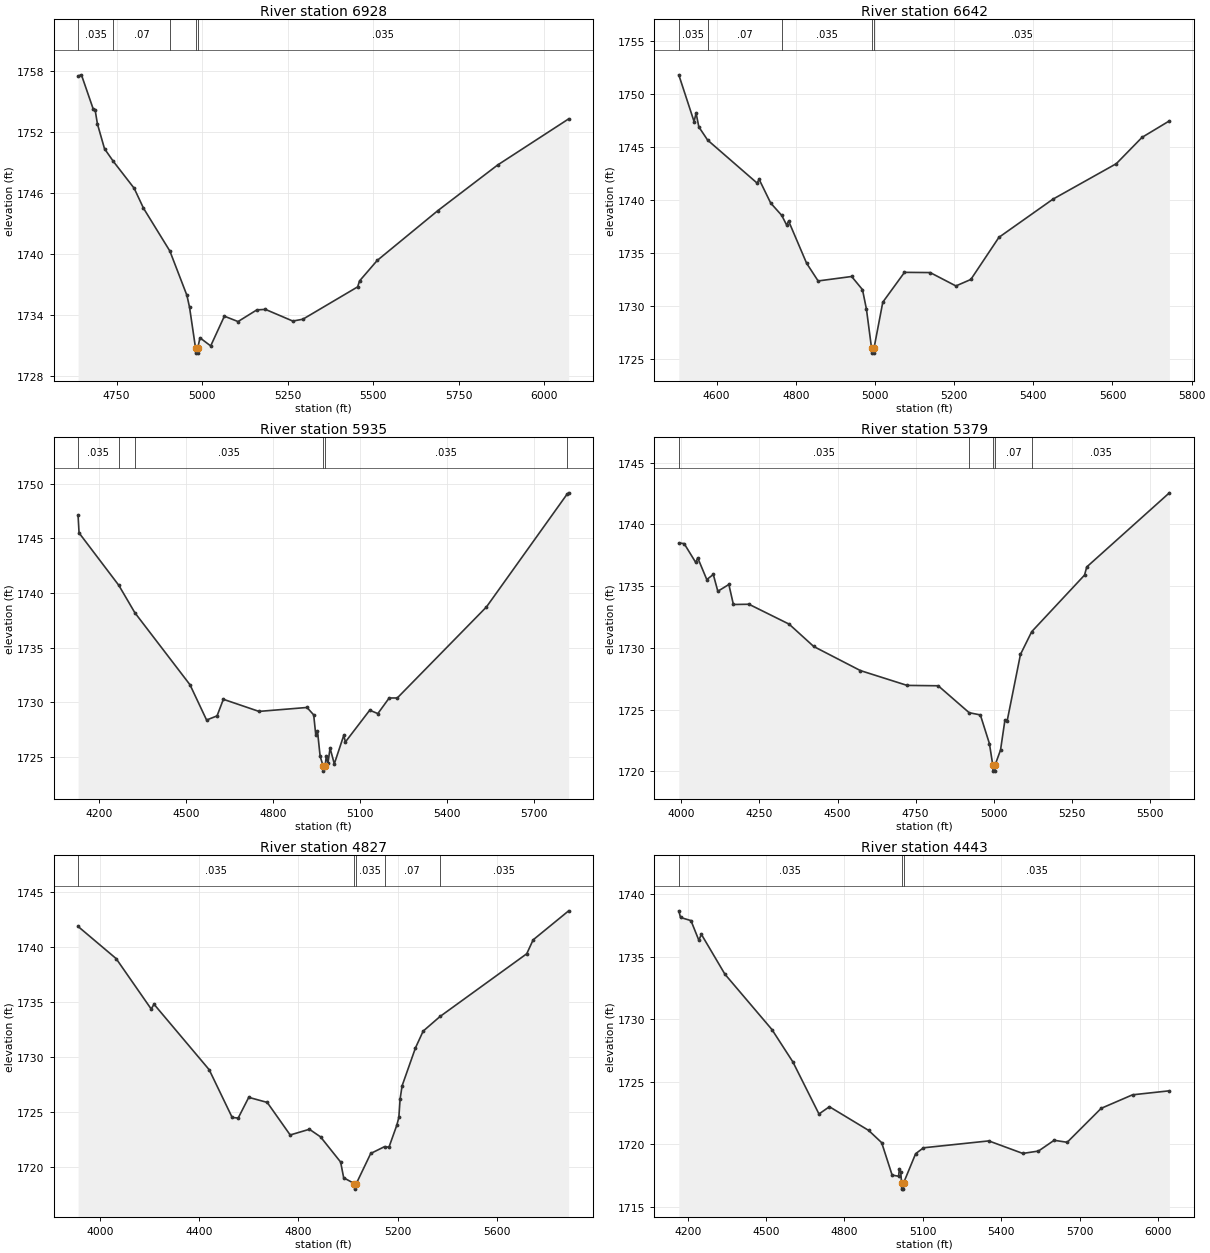
Type RM Length L Ch R = 1,6928,286,286,286
BEGIN DESCRIPTION:
Mapping XS 13a36013
END DESCRIPTION:
XS GIS Cut Line= 3
      1681610.34      6980235.51      1681956.67      6980141.77
      1682995.76      6979863.12
#Sta/Elev= 30
  4637.1 1757.52  4646.9 1757.63  4681.6 1754.24  4686.8 1754.20  4693.7 1752.79
  4714.4 1750.35  4740.3 1749.10  4801.2 1746.45  4828.4 1744.49  4905.5 1740.27
  4955.4 1735.90  4963.1 1734.72  4980.6 1730.71  4981.1 1730.21  4986.6 1730.21
  4987.1 1730.71  4993.5 1731.72  5024.9 1730.92  5064.9 1733.85  5104.9 1733.32
  5159.8 1734.47  5184.9 1734.52  5265.0 1733.37  5294.4 1733.55  5454.7 1736.74
  5460.1 1737.32  5511.8 1739.34  5689.5 1744.26  5863.8 1748.74  6071.7 1753.29
#Mann=5,-1,0
  4637.1   0.035       0  4740.3    0.07       0  4905.5   0.035       0
  4980.6   0.035       0  4987.1   0.035       0
Bank Sta=4980.6,4987.1
Exp/Cntr=0.3,0.1

Type RM Length L Ch R = 1,6642,707,707,707
BEGIN DESCRIPTION:
Mapping XS 5b709490
END DESCRIPTION:
XS GIS Cut Line= 3
      1681614.72      6980438.31      1682101.69      6980375.81
      1682816.01      6980152.43
#Sta/Elev= 30
  4504.3 1751.77  4542.9 1747.37  4548.0 1748.16  4555.0 1746.86  4577.2 1745.62
  4702.2 1741.57  4707.2 1741.93  4736.5 1739.69  4764.5 1738.52  4776.7 1737.62
  4781.8 1737.99  4827.2 1734.02  4856.3 1732.35  4941.0 1732.77  4968.4 1731.53
  4978.4 1729.69  4991.2 1726.05  4991.7 1725.55  4997.2 1725.55  4997.7 1726.05
  5019.7 1730.35  5074.5 1733.16  5139.4 1733.14  5204.4 1731.88  5242.1 1732.49
  5313.1 1736.46  5449.3 1740.05  5609.7 1743.40  5674.7 1745.88  5743.7 1747.43
#Mann=5,-1,0
  4504.3   0.035       0  4577.2    0.07       0  4764.5   0.035       0
  4991.2   0.035       0  4997.7   0.035       0
Bank Sta=4991.2,4997.7
Exp/Cntr=0.3,0.1

Type RM Length L Ch R = 1,5935,556,556,556
BEGIN DESCRIPTION:
Mapping XS 53a79de7
END DESCRIPTION:
XS GIS Cut Line= 3
      1681527.00      6980501.22      1682254.03      6980980.85
      1682987.56      6981347.61
#Sta/Elev= 30
  4128.1 1747.11  4131.5 1745.50  4268.5 1740.70  4323.8 1738.19  4513.9 1731.59
  4571.1 1728.36  4607.2 1728.74  4628.9 1730.26  4751.7 1729.15  4917.3 1729.51
  4940.3 1728.83  4947.4 1727.01  4953.4 1727.34  4962.5 1725.04  4972.6 1724.18
  4973.1 1723.68  4979.9 1724.18  4983.6 1725.04  4989.5 1724.42  4996.7 1725.79
  5011.4 1724.35  5044.0 1726.96  5049.6 1726.35  5133.4 1729.26  5161.4 1728.95
  5200.5 1730.38  5228.4 1730.38  5535.9 1738.72  5813.5 1749.04  5819.2 1749.17
#Mann=6,-1,0
  4128.1   0.035       0  4268.5    0.07       0  4323.8   0.035       0
  4972.6   0.035       0  4979.9   0.035       0  5813.5    0.07       0
Bank Sta=4972.6,4979.9
Exp/Cntr=0.3,0.1

Type RM Length L Ch R = 1,5379,552,552,552
BEGIN DESCRIPTION:
Mapping XS 6ac5820a
END DESCRIPTION:
XS GIS Cut Line= 3
      1681433.17      6980634.70      1682051.67      6981435.49
      1682437.93      6981839.11
#Sta/Elev= 30
  3991.7 1738.49  4008.9 1738.44  4046.0 1736.91  4052.3 1737.29  4081.3 1735.53
  4102.2 1735.94  4116.7 1734.58  4152.0 1735.13  4166.5 1733.51  4216.3 1733.53
  4344.9 1731.92  4423.7 1730.11  4573.1 1728.16  4722.6 1726.96  4822.2 1726.93
  4921.3 1724.75  4957.1 1724.57  4986.1 1722.25  4996.8 1720.52  4997.3 1720.02
  5003.8 1720.02  5004.3 1720.52  5021.7 1721.73  5035.8 1724.16  5043.1 1724.11
  5085.5 1729.47  5121.5 1731.31  5290.6 1735.89  5297.7 1736.55  5562.2 1742.55
#Mann=5,-1,0
  3991.7   0.035       0  4921.3    0.07       0  4996.8    0.07       0
  5004.3    0.07       0  5121.5   0.035       0
Bank Sta=4996.8,5004.3
Exp/Cntr=0.3,0.1

Type RM Length L Ch R = 1,4827,384,384,384
BEGIN DESCRIPTION:
Mapping XS e0e01145
END DESCRIPTION:
XS GIS Cut Line= 3
      1681236.69      6980660.90      1681608.80      6981684.06
      1682449.05      6981979.19
#Sta/Elev= 30
  3910.7 1741.87  4064.3 1738.95  4205.6 1734.37  4217.2 1734.80  4439.7 1728.85
  4532.5 1724.51  4556.7 1724.46  4599.3 1726.34  4673.8 1725.88  4766.5 1722.92
  4844.0 1723.44  4888.9 1722.75  4970.0 1720.46  4982.3 1719.03  5025.7 1718.50
  5026.2 1718.00  5033.2 1718.50  5091.4 1721.24  5147.1 1721.86  5165.0 1721.81
  5196.8 1723.82  5204.8 1724.51  5210.1 1726.22  5218.0 1727.39  5272.0 1730.84
  5303.0 1732.36  5371.2 1733.69  5720.9 1739.39  5746.6 1740.65  5890.0 1743.29
#Mann=5,-1,0
  3910.7   0.035       0  5025.7   0.035       0  5033.2   0.035       0
  5147.1    0.07       0  5371.2   0.035       0
Bank Sta=5025.7,5033.2
Exp/Cntr=0.3,0.1

Type RM Length L Ch R = 1,4443,206,206,206
BEGIN DESCRIPTION:
Mapping XS 91aefb16
END DESCRIPTION:
XS GIS Cut Line= 3
      1681262.73      6980861.44      1681260.13      6981702.58
      1681239.30      6982739.03
#Sta/Elev= 30
  4165.9 1738.65  4172.5 1738.12  4212.5 1737.87  4242.5 1736.31  4252.5 1736.77
  4342.5 1733.59  4522.5 1729.17  4602.5 1726.59  4702.5 1722.43  4742.5 1723.01
  4892.5 1721.12  4942.5 1720.14  4982.5 1717.55  5007.0 1717.46  5010.5 1718.06
  5015.5 1717.76  5018.6 1716.93  5019.1 1716.43  5025.9 1716.43  5026.4 1716.93
  5072.5 1719.26  5102.5 1719.73  5352.5 1720.28  5482.6 1719.28  5542.6 1719.47
  5602.6 1720.33  5652.6 1720.17  5782.6 1722.88  5902.6 1723.96  6043.7 1724.28
#Mann=3,-1,0
  4165.9   0.035       0  5018.6   0.035       0  5026.4   0.035       0
Bank Sta=5018.6,5026.4
Exp/Cntr=0.3,0.1