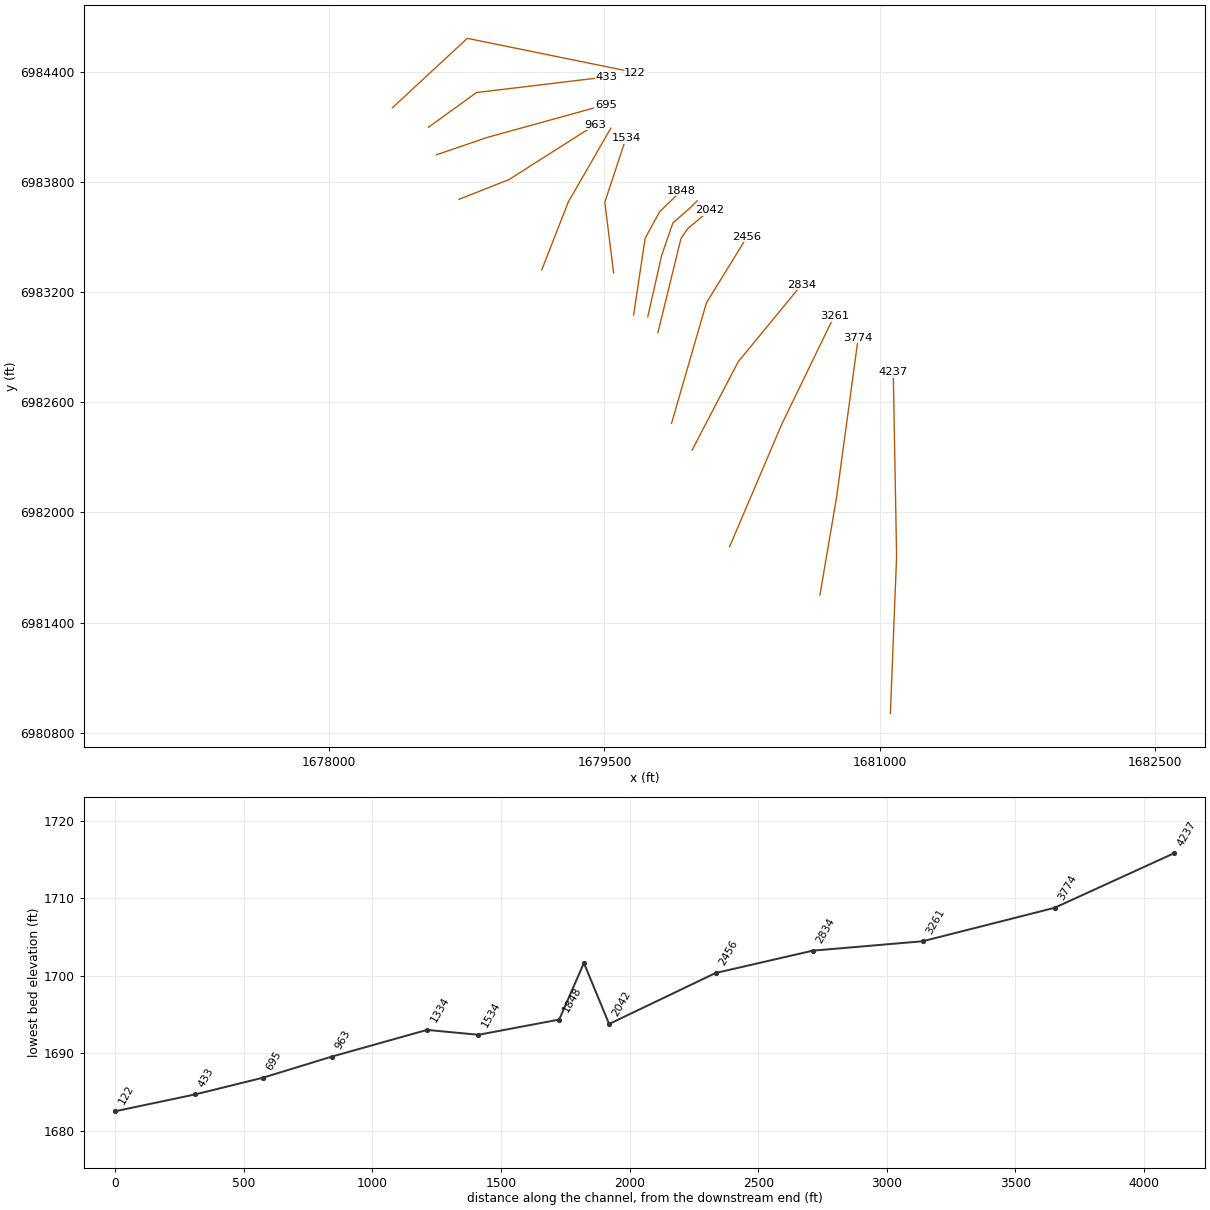
HEC-RAS study Chimney Creek 1166.prj: Chimney Creek 1166 Base Level Engineering

--- Chimney Creek 1166.g01 (geometry) --- (continued)

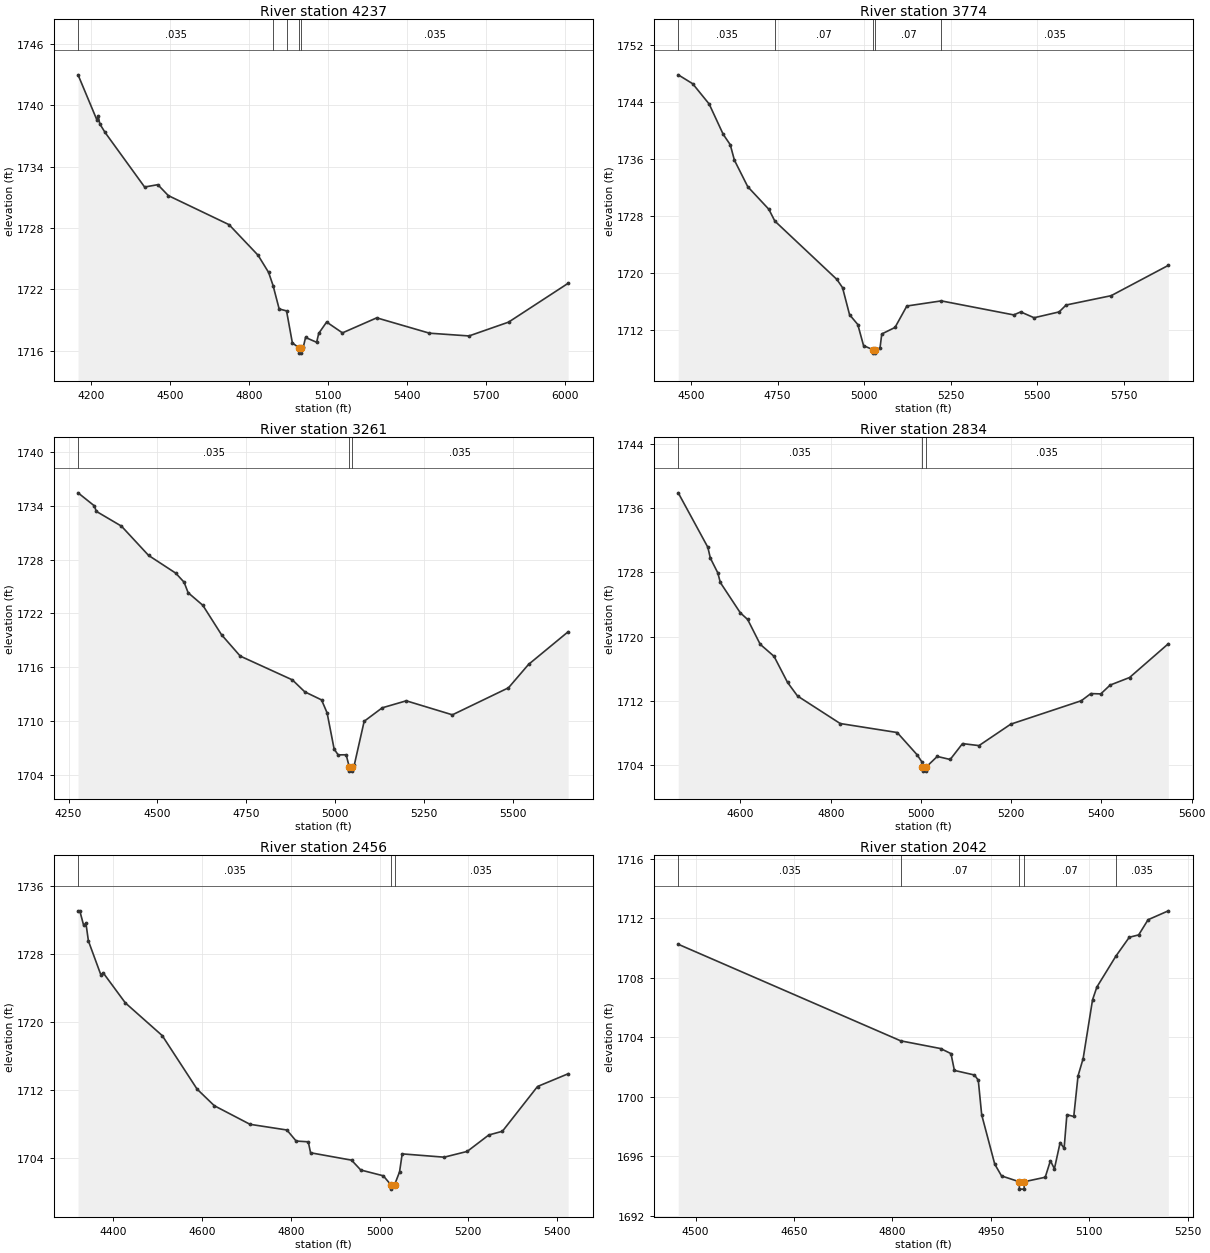
Type RM Length L Ch R = 1,4237,463,463,463
BEGIN DESCRIPTION:
Mapping XS 9f5cb4c8
END DESCRIPTION:
XS GIS Cut Line= 3
      1681057.00      6980905.68      1681090.86      6981759.87
      1681072.65      6982764.04
#Sta/Elev= 30
  4152.1 1742.97  4223.6 1738.56  4228.6 1738.97  4234.5 1738.18  4254.5 1737.34
  4404.6 1732.00  4454.7 1732.23  4494.7 1731.16  4724.9 1728.32  4835.0 1725.33
  4875.0 1723.65  4892.0 1722.36  4915.0 1720.08  4943.0 1719.89  4965.1 1716.76
  4991.2 1716.26  4991.7 1715.76  4998.5 1715.76  4999.0 1716.26  5007.0 1716.40
  5015.1 1717.29  5057.2 1716.82  5065.1 1717.69  5095.1 1718.80  5155.1 1717.74
  5285.1 1719.21  5485.2 1717.71  5635.2 1717.44  5785.2 1718.79  6011.3 1722.59
#Mann=5,-1,0
  4152.1   0.035       0  4892.0    0.07       0  4943.0   0.035       0
  4991.2   0.035       0  4999.0   0.035       0
Bank Sta=4991.2,4999
Exp/Cntr=0.3,0.1

Type RM Length L Ch R = 1,3774,513,513,513
BEGIN DESCRIPTION:
Mapping XS a1bbbb37
END DESCRIPTION:
XS GIS Cut Line= 3
      1680673.33      6981549.84      1680764.47      6982086.26
      1680881.66      6982950.85
#Sta/Elev= 30
  4462.8 1747.85  4504.6 1746.60  4552.2 1743.75  4592.8 1739.49  4613.1 1738.04
  4625.2 1735.86  4663.8 1732.13  4724.7 1728.96  4742.1 1727.30  4921.5 1719.10
  4937.7 1717.95  4958.0 1714.15  4981.8 1712.77  4998.5 1709.80  5024.9 1709.25
  5025.4 1708.75  5032.3 1708.75  5032.8 1709.25  5046.0 1709.46  5051.1 1711.44
  5089.4 1712.36  5123.6 1715.37  5223.1 1716.09  5432.5 1714.12  5452.7 1714.54
  5491.4 1713.72  5563.7 1714.54  5583.9 1715.51  5714.1 1716.82  5879.4 1721.08
#Mann=5,-1,0
  4462.8   0.035       0  4742.1    0.07       0  5024.9    0.07       0
  5032.8    0.07       0  5223.1   0.035       0
Bank Sta=5024.9,5032.8
Exp/Cntr=0.3,0.1

Type RM Length L Ch R = 1,3261,427,427,427
BEGIN DESCRIPTION:
Mapping XS 616bbdf1
END DESCRIPTION:
XS GIS Cut Line= 3
      1680181.14      6981812.84      1680464.99      6982479.49
      1680750.73      6983069.14
#Sta/Elev= 30
  4276.7 1735.43  4322.6 1733.98  4328.0 1733.37  4398.9 1731.72  4475.3 1728.46
  4551.6 1726.49  4575.2 1725.48  4586.6 1724.31  4627.9 1722.91  4680.6 1719.63
  4733.3 1717.25  4880.1 1714.60  4915.0 1713.27  4962.3 1712.37  4977.9 1710.92
  4997.7 1706.89  5009.0 1706.25  5031.5 1706.26  5040.1 1704.94  5040.6 1704.44
  5047.5 1704.44  5048.0 1704.94  5054.1 1705.07  5082.2 1709.99  5133.0 1711.49
  5200.7 1712.27  5330.6 1710.71  5488.5 1713.72  5544.9 1716.32  5656.5 1719.96
#Mann=3,-1,0
  4276.7   0.035       0  5040.1   0.035       0  5048.0   0.035       0
Bank Sta=5040.1,5048
Exp/Cntr=0.3,0.1

Type RM Length L Ch R = 1,2834,378,378,378
BEGIN DESCRIPTION:
Mapping XS e0525775
END DESCRIPTION:
XS GIS Cut Line= 3
      1679977.14      6982339.72      1680227.14      6982818.90
      1680573.49      6983240.76
#Sta/Elev= 30
  4462.0 1737.90  4527.6 1731.12  4533.2 1729.77  4549.7 1727.93  4555.3 1726.73
  4599.5 1722.96  4615.9 1722.12  4643.7 1719.03  4674.4 1717.53  4704.3 1714.28
  4726.4 1712.59  4821.0 1709.16  4947.3 1708.04  4991.4 1705.27  5002.5 1704.34
  5003.4 1703.73  5003.9 1703.23  5010.9 1703.23  5011.4 1703.73  5036.1 1705.06
  5064.8 1704.68  5092.1 1706.66  5128.6 1706.41  5199.0 1709.08  5355.4 1712.00
  5376.5 1712.89  5398.5 1712.85  5419.3 1713.95  5462.3 1714.89  5548.3 1719.10
#Mann=3,-1,0
  4462.0   0.035       0  5003.4   0.035       0  5011.4   0.035       0
Bank Sta=5003.4,5011.4
Exp/Cntr=0.3,0.1

Type RM Length L Ch R = 1,2456,414,414,414
BEGIN DESCRIPTION:
Mapping XS 3bc2f0a6
END DESCRIPTION:
XS GIS Cut Line= 3
      1679865.16      6982485.56      1680055.27      6983141.82
      1680276.62      6983501.18
#Sta/Elev= 30
  4320.1 1733.11  4324.0 1733.11  4332.7 1731.41  4337.9 1731.64  4343.5 1729.56
  4371.5 1725.58  4376.7 1725.82  4426.8 1722.27  4510.0 1718.42  4588.6 1712.12
  4627.4 1710.17  4707.9 1707.98  4791.1 1707.31  4812.0 1706.01  4839.3 1705.92
  4844.5 1704.63  4936.9 1703.76  4957.7 1702.60  5008.5 1701.92  5025.8 1700.85
  5026.3 1700.35  5033.9 1700.85  5045.2 1702.39  5051.1 1704.50  5145.8 1704.11
  5197.8 1704.79  5246.3 1706.72  5277.1 1707.16  5356.3 1712.43  5425.4 1713.93
#Mann=3,-1,0
  4320.1   0.035       0  5025.8   0.035       0  5033.9   0.035       0
Bank Sta=5025.8,5033.9
Exp/Cntr=0.3,0.1

Type RM Length L Ch R = 1,2042,98,98,98
BEGIN DESCRIPTION:
Mapping XS 7791b1ad
END DESCRIPTION:
XS GIS Cut Line= 4
      1679790.94      6982979.57      1679916.81      6983492.84
      1679954.79      6983547.09      1680071.55      6983644.56
#Sta/Elev= 30
  4473.6 1710.26  4812.6 1703.76  4873.5 1703.24  4889.2 1702.90  4894.4 1701.77
  4925.0 1701.46  4930.8 1701.11  4936.0 1698.78  4955.9 1695.46  4966.2 1694.67
  4993.0 1694.28  4993.5 1693.78  5000.6 1693.78  5001.1 1694.28  5032.8 1694.58
  5040.7 1695.69  5046.8 1695.15  5055.5 1696.91  5061.6 1696.53  5065.8 1698.79
  5076.3 1698.67  5082.8 1701.40  5090.6 1702.57  5104.9 1706.52  5111.5 1707.38
  5140.3 1709.45  5160.9 1710.73  5175.2 1710.89  5189.5 1711.91  5220.4 1712.51
#Mann=5,-1,0
  4473.6   0.035       0  4812.6    0.07       0  4993.0    0.07       0
  5001.1    0.07       0  5140.3   0.035       0
Bank Sta=4993,5001.1
Exp/Cntr=0.3,0.1

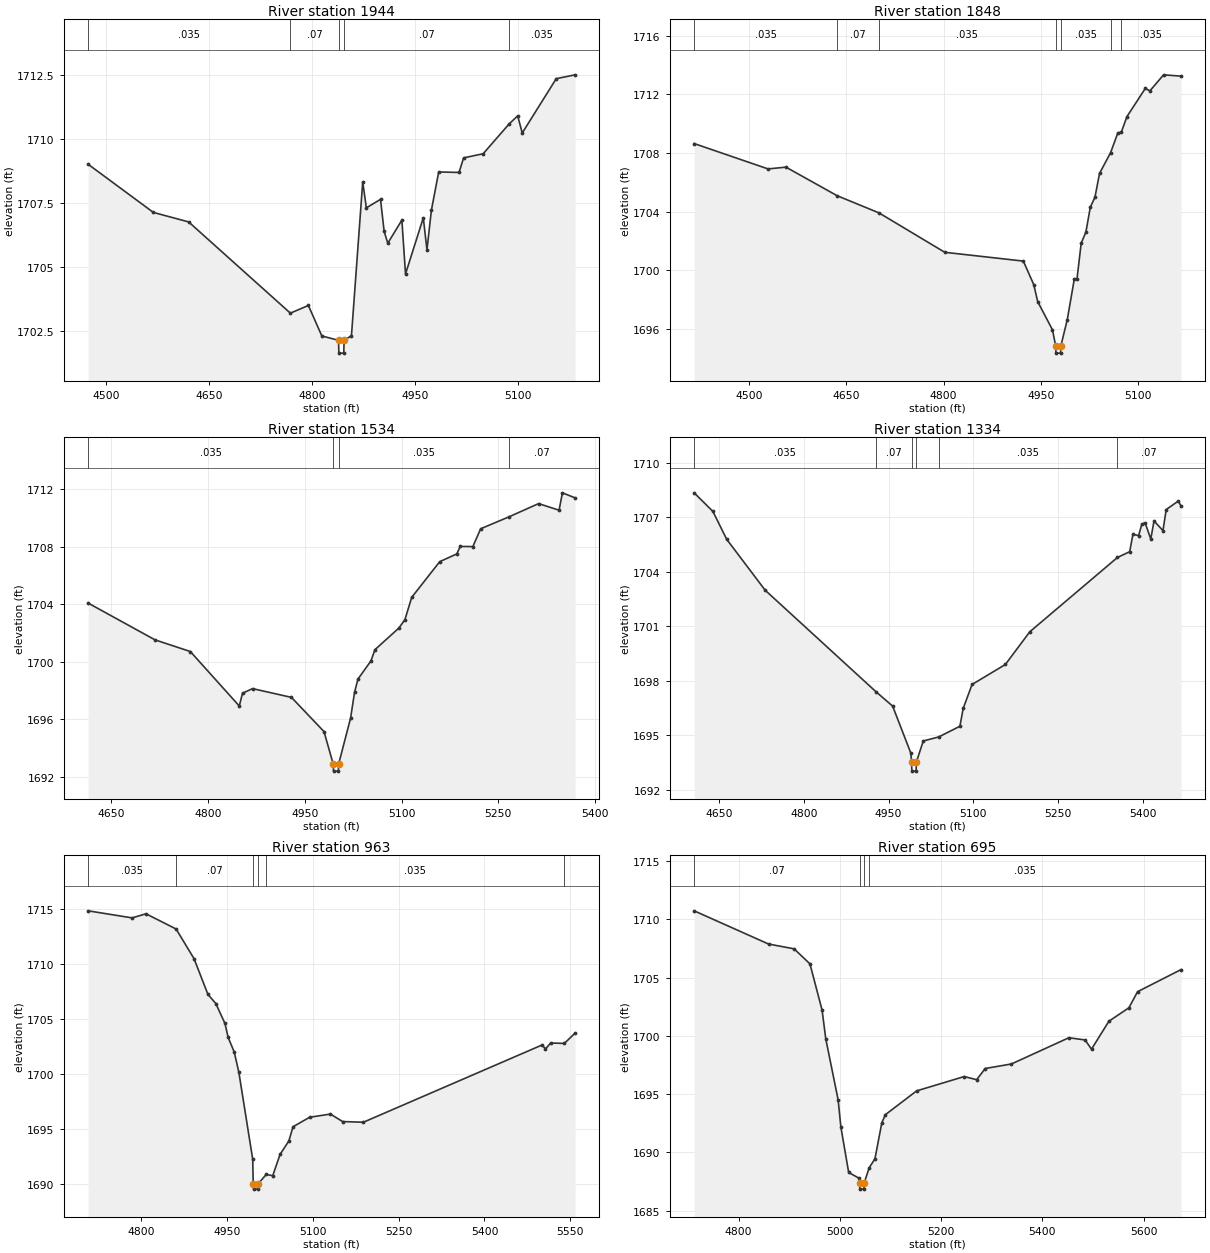
Type RM Length L Ch R = 1,1944,96,96,96
BEGIN DESCRIPTION:
Mapping XS 79d6fa91
END DESCRIPTION:
XS GIS Cut Line= 5
      1679735.61      6983065.35      1679811.56      6983400.61
      1679872.33      6983576.39      1679960.22      6983653.43
      1680004.73      6983696.85
#Sta/Elev= 30
  4474.3 1709.01  4569.3 1707.13  4620.6 1706.76  4768.7 1703.20  4794.9 1703.50
  4814.5 1702.31  4838.8 1702.14  4839.3 1701.64  4846.4 1701.64  4846.9 1702.14
  4857.6 1702.32  4874.0 1708.32  4879.3 1707.31  4899.9 1707.64  4905.2 1706.39
  4910.5 1705.93  4931.0 1706.83  4936.3 1704.73  4962.2 1706.92  4967.5 1705.67
  4974.0 1707.22  4984.6 1708.71  5014.2 1708.69  5020.9 1709.26  5049.3 1709.42
  5087.0 1710.58  5099.6 1710.90  5106.2 1710.23  5155.7 1712.35  5183.1 1712.50
#Mann=5,-1,0
  4474.3   0.035       0  4768.7    0.07       0  4838.8    0.07       0
  4846.9    0.07       0  5087.0   0.035       0
Bank Sta=4838.8,4846.9
Exp/Cntr=0.3,0.1

Type RM Length L Ch R = 1,1848,314,314,314
BEGIN DESCRIPTION:
Mapping XS a3812300
END DESCRIPTION:
XS GIS Cut Line= 4
      1679658.56      6983075.05      1679721.50      6983493.92
      1679800.71      6983638.24      1679918.97      6983752.15
#Sta/Elev= 30
  4414.6 1708.65  4528.8 1706.92  4556.5 1707.04  4635.6 1705.09  4700.2 1703.92
  4801.9 1701.23  4923.3 1700.63  4939.4 1699.02  4945.5 1697.86  4968.3 1695.94
  4973.2 1694.85  4973.7 1694.35  4980.8 1694.35  4981.3 1694.85  4991.1 1696.62
  5002.1 1699.42  5006.2 1699.42  5012.7 1701.86  5019.9 1702.60  5026.8 1704.31
  5034.0 1705.00  5041.0 1706.61  5058.1 1708.03  5069.3 1709.38  5074.7 1709.43
  5083.4 1710.49  5111.7 1712.41  5118.9 1712.25  5140.0 1713.34  5167.0 1713.25
#Mann=7,-1,0
  4414.6   0.035       0  4635.6    0.07       0  4700.2   0.035       0
  4973.2   0.035       0  4981.3   0.035       0  5058.1    0.07       0
  5074.7   0.035       0
Bank Sta=4973.2,4981.3
Exp/Cntr=0.3,0.1

Type RM Length L Ch R = 1,1534,200,200,200
BEGIN DESCRIPTION:
Mapping XS 719a425a
END DESCRIPTION:
XS GIS Cut Line= 3
      1679549.44      6983304.96      1679501.70      6983689.52
      1679617.15      6984038.50
#Sta/Elev= 30
  4614.0 1704.08  4717.8 1701.52  4772.5 1700.71  4848.4 1696.92  4853.4 1697.81
  4869.0 1698.13  4929.3 1697.52  4979.8 1695.14  4994.0 1692.89  4994.5 1692.39
  5002.0 1692.39  5002.5 1692.89  5021.0 1696.08  5027.1 1697.86  5032.4 1698.79
  5052.6 1700.06  5058.8 1700.84  5095.8 1702.34  5105.2 1702.92  5115.8 1704.48
  5159.2 1706.96  5185.7 1707.50  5191.0 1708.02  5210.6 1708.01  5222.7 1709.25
  5266.1 1710.07  5312.6 1711.00  5344.3 1710.54  5349.5 1711.75  5369.1 1711.40
#Mann=4,-1,0
  4614.0   0.035       0  4994.0   0.035       0  5002.5   0.035       0
  5266.1    0.07       0
Bank Sta=4994,5002.5
Exp/Cntr=0.3,0.1

Type RM Length L Ch R = 1,1334,371,371,371
BEGIN DESCRIPTION:
Mapping XS 24da1c92
END DESCRIPTION:
XS GIS Cut Line= 3
      1679158.37      6983321.01      1679302.91      6983690.83
      1679534.64      6984093.10
#Sta/Elev= 30
  4606.0 1708.34  4639.1 1707.32  4663.6 1705.78  4731.6 1702.98  4928.0 1697.38
  4957.1 1696.60  4989.3 1694.01  4990.6 1693.52  4991.1 1693.02  4998.6 1693.02
  4999.1 1693.52  5011.3 1694.68  5038.5 1694.90  5076.1 1695.49  5081.9 1696.47
  5097.6 1697.79  5156.5 1698.89  5199.7 1700.69  5354.7 1704.78  5376.4 1705.10
  5382.1 1706.05  5392.2 1705.99  5397.9 1706.61  5403.7 1706.69  5413.7 1705.80
  5419.5 1706.79  5435.3 1706.26  5441.0 1707.42  5462.6 1707.89  5467.3 1707.60
#Mann=6,-1,0
  4606.0   0.035       0  4928.0    0.07       0  4990.6    0.07       0
  4999.1    0.07       0  5038.5   0.035       0  5354.7    0.07       0
Bank Sta=4990.6,4999.1
Exp/Cntr=0.3,0.1

Type RM Length L Ch R = 1,963,268,268,268
BEGIN DESCRIPTION:
Mapping XS fc845d3c
END DESCRIPTION:
XS GIS Cut Line= 3
      1678707.44      6983705.20      1678980.02      6983812.85
      1679450.97      6984112.38
#Sta/Elev= 30
  4707.2 1714.82  4784.0 1714.18  4808.4 1714.55  4861.0 1713.17  4892.3 1710.48
  4916.6 1707.24  4930.4 1706.41  4946.4 1704.60  4951.9 1703.34  4962.6 1702.01
  4970.7 1700.16  4994.9 1692.28  4995.8 1690.07  4996.3 1689.57  5004.2 1689.57
  5004.7 1690.07  5018.5 1690.90  5029.9 1690.79  5042.7 1692.72  5058.0 1693.93
  5065.4 1695.23  5094.4 1696.09  5130.8 1696.38  5152.0 1695.70  5188.4 1695.64
  5500.8 1702.65  5506.7 1702.29  5515.8 1702.83  5539.6 1702.79  5558.4 1703.72
#Mann=6,-1,0
  4707.2   0.035       0  4861.0    0.07       0  4995.8    0.07       0
  5004.7    0.07       0  5018.5   0.035       0  5539.6    0.07       0
Bank Sta=4995.8,5004.7
Exp/Cntr=0.3,0.1

Type RM Length L Ch R = 1,695,262,262,262
BEGIN DESCRIPTION:
Mapping XS 0032eb9e
END DESCRIPTION:
XS GIS Cut Line= 3
      1678585.92      6983948.26      1678860.23      6984042.01
      1679507.80      6984220.83
#Sta/Elev= 30
  4712.3 1710.73  4859.3 1707.88  4909.7 1707.47  4941.0 1706.18  4965.0 1702.21
  4972.3 1699.74  4996.7 1694.51  5002.1 1692.18  5017.5 1688.28  5038.3 1687.78
  5039.0 1687.35  5039.5 1686.85  5047.4 1686.85  5047.9 1687.35  5058.0 1688.68
  5069.4 1689.45  5083.0 1692.55  5090.1 1693.24  5151.7 1695.28  5245.7 1696.51
  5270.3 1696.24  5287.2 1697.20  5339.0 1697.59  5452.4 1699.84  5484.4 1699.65
  5497.1 1698.86  5531.5 1701.26  5571.0 1702.41  5588.1 1703.79  5674.0 1705.69
#Mann=4,-1,0
  4712.3    0.07       0  5039.0    0.07       0  5047.9    0.07       0
  5058.0   0.035       0
Bank Sta=5039,5047.9
Exp/Cntr=0.3,0.1

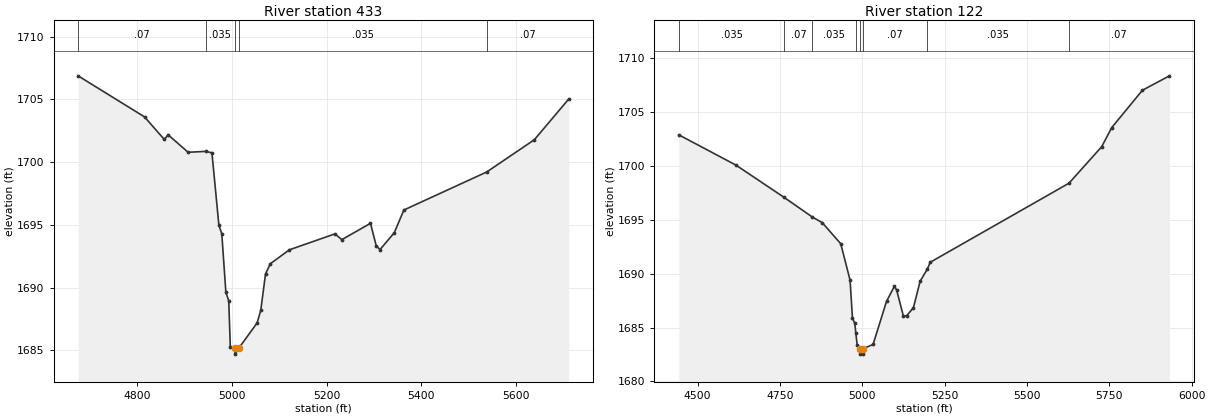
Type RM Length L Ch R = 1,433,311,311,311
BEGIN DESCRIPTION:
Mapping XS 66038528
END DESCRIPTION:
XS GIS Cut Line= 3
      1678540.79      6984097.57      1678802.94      6984286.80
      1679510.64      6984371.80
#Sta/Elev= 30
  4675.0 1706.88  4815.3 1703.61  4857.1 1701.81  4865.2 1702.18  4907.4 1700.79
  4944.1 1700.86  4957.7 1700.75  4972.4 1694.97  4978.5 1694.30  4987.1 1689.64
  4993.2 1688.95  4996.5 1685.27  5006.0 1685.21  5006.5 1684.71  5014.9 1685.21
  5053.0 1687.19  5060.8 1688.19  5070.9 1691.11  5081.0 1691.91  5121.2 1693.02
  5217.5 1694.29  5232.0 1693.83  5292.5 1695.13  5304.7 1693.33  5312.6 1693.04
  5342.8 1694.38  5363.0 1696.19  5538.0 1699.22  5638.6 1701.79  5711.1 1705.03
#Mann=5,-1,0
  4675.0    0.07       0  4944.1   0.035       0  5006.0   0.035       0
  5014.9   0.035       0  5538.0    0.07       0
Bank Sta=5006,5014.9
Exp/Cntr=0.3,0.1

Type RM Length L Ch R = 1,122,0,0,0
BEGIN DESCRIPTION:
Chimney Creek 1166 1.0
END DESCRIPTION:
XS GIS Cut Line= 3
      1678344.63      6984203.49      1678752.77      6984582.08
      1679666.59      6984395.83
#Sta/Elev= 30
  4443.3 1702.90  4616.7 1700.09  4763.0 1697.09  4849.0 1695.26  4878.6 1694.75
  4934.8 1692.79  4963.1 1689.41  4970.4 1685.88  4977.3 1685.41  4980.7 1684.47
  4984.6 1683.40  4993.7 1683.04  4994.2 1682.54  5002.1 1682.54  5002.6 1683.04
  5032.9 1683.44  5073.7 1687.43  5097.4 1688.83  5104.3 1688.51  5124.7 1686.10
  5134.9 1686.10  5155.4 1686.85  5175.8 1689.31  5197.9 1690.45  5206.4 1691.07
  5627.6 1698.41  5726.9 1701.80  5757.5 1703.58  5850.5 1707.04  5932.6 1708.38
#Mann=8,-1,0
  4443.3   0.035       0  4763.0    0.07       0  4849.0   0.035       0
  4980.7    0.07       0  4993.7    0.07       0  5002.6    0.07       0
  5197.9   0.035       0  5627.6    0.07       0
Bank Sta=4993.7,5002.6
Exp/Cntr=0.3,0.1

Chan Stop Cuts=-1