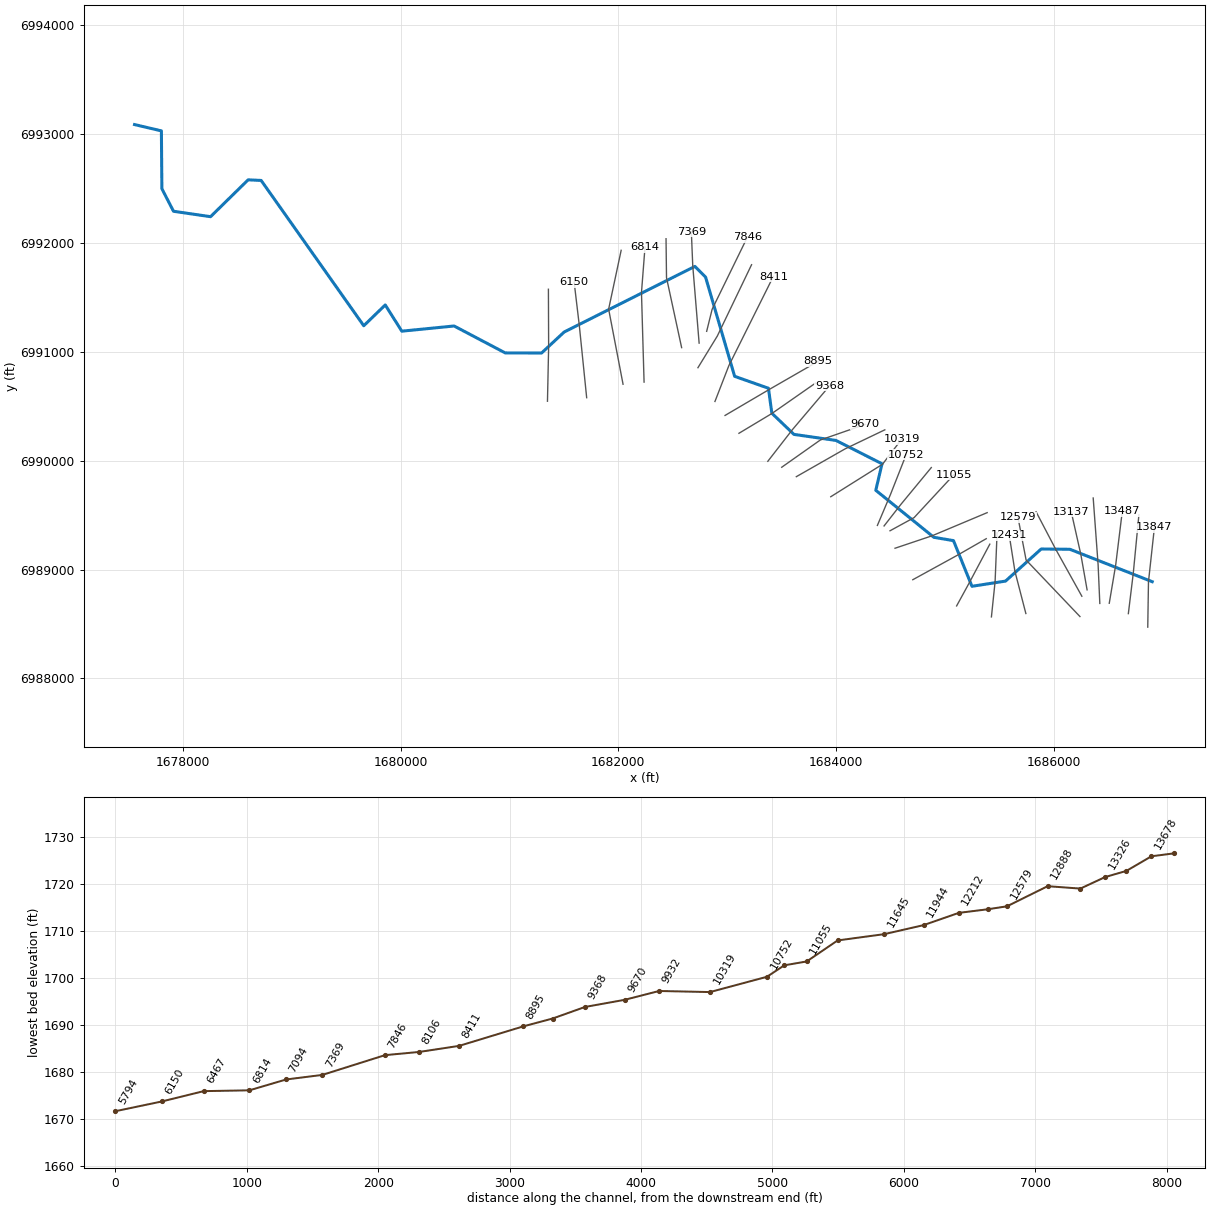
--- Chimney Creek 1167.prj (project) ---

Proj Title=Chimney Creek 1167 Base Level Engineering
Current Plan=p01
Default Exp/Contr=0.3,0.1
English Units
Geom File=g01
Flow File=f01
Plan File=p01
BEGIN DESCRIPTION:
Chimney Creek 1167
END DESCRIPTION:

--- Chimney Creek 1167.p01 (plan) ---

Plan Title=Multiple Run
Short Identifier=Multiple
Geom File=g01
Flow File=f01
Subcritical Flow
K Sum by GR= 0
Std Step Tol= 0.01
Critical Tol= 0.01
Num of Std Step Trials= 20
Max Error Tol= 0.3
Flow Tol Ratio= 0.001
Split Flow NTrial= 30
Split Flow Tol= 0.02
Split Flow Ratio= 0.02
Log Output Level= 0
Friction Slope Method= 1
Unsteady Friction Slope Method= 2
Unsteady Bridges Friction Slope Method= 1
Parabolic Critical Depth
Global Vel Dist=  1 , 1 , 1
Global Log Level= 0
CheckData=True
Encroach Param= -1, 0, 0, 0
BEGIN DESCRIPTION:
Multiple Run
END DESCRIPTION:

--- Chimney Creek 1167.f01 (steady flow) ---

Flow Title=Multiple
Number of Profiles=7
Profile Names=10-year,25-year,50-year,1pct_min,100-year,1pct_plu,500-year
River Rch & RM= Chimney Creek 11,Reach-1,13847
     283     394     487     301     600    1196     918
River Rch & RM= Chimney Creek 11,Reach-1,13487
     455     648     811     506    1009    2013    1579
River Rch & RM= Chimney Creek 11,Reach-1,1774
     659     955    1211     763    1523    3038    2438
Boundary for River Rch & Prof#=Chimney Creek 11,Reach-1,1
Up Type=0
Dn Type=3
Dn Slope=0.005
Boundary for River Rch & Prof#=Chimney Creek 11,Reach-1,2
Up Type=0
Dn Type=3
Dn Slope=0.005
Boundary for River Rch & Prof#=Chimney Creek 11,Reach-1,3
Up Type=0
Dn Type=3
Dn Slope=0.005
Boundary for River Rch & Prof#=Chimney Creek 11,Reach-1,4
Up Type=0
Dn Type=3
Dn Slope=0.005
Boundary for River Rch & Prof#=Chimney Creek 11,Reach-1,5
Up Type=0
Dn Type=3
Dn Slope=0.005
Boundary for River Rch & Prof#=Chimney Creek 11,Reach-1,6
Up Type=0
Dn Type=3
Dn Slope=0.005
Boundary for River Rch & Prof#=Chimney Creek 11,Reach-1,7
Up Type=0
Dn Type=3
Dn Slope=0.005

--- Chimney Creek 1167.g01 (geometry) ---

Geom Title=Existing Conditions

River Reach=Chimney Creek 11,Reach-1
Reach XY= 30
      1686905.00      6988888.00      1686149.07      6989185.76
      1685884.82      6989188.43      1685557.43      6988893.52
      1685248.79      6988845.80      1685079.02      6989265.34
      1684898.81      6989295.82      1684365.28      6989727.84
      1684422.60      6989971.36      1683999.14      6990185.93
      1683613.44      6990241.41      1683410.46      6990435.55
      1683379.03      6990665.35      1683068.62      6990774.76
      1682801.39      6991686.52      1682703.38      6991784.88
      1681502.70      6991182.17      1681294.57      6990989.05
      1680960.68      6990990.01      1680491.08      6991237.32
      1680010.61      6991189.73      1679858.43      6991430.61
      1679661.05      6991239.58      1678718.31      6992574.54
      1678598.79      6992580.24      1678253.54      6992241.53
      1677913.02      6992291.31      1677806.20      6992498.50
      1677801.78      6993030.02      1677555.00      6993088.00

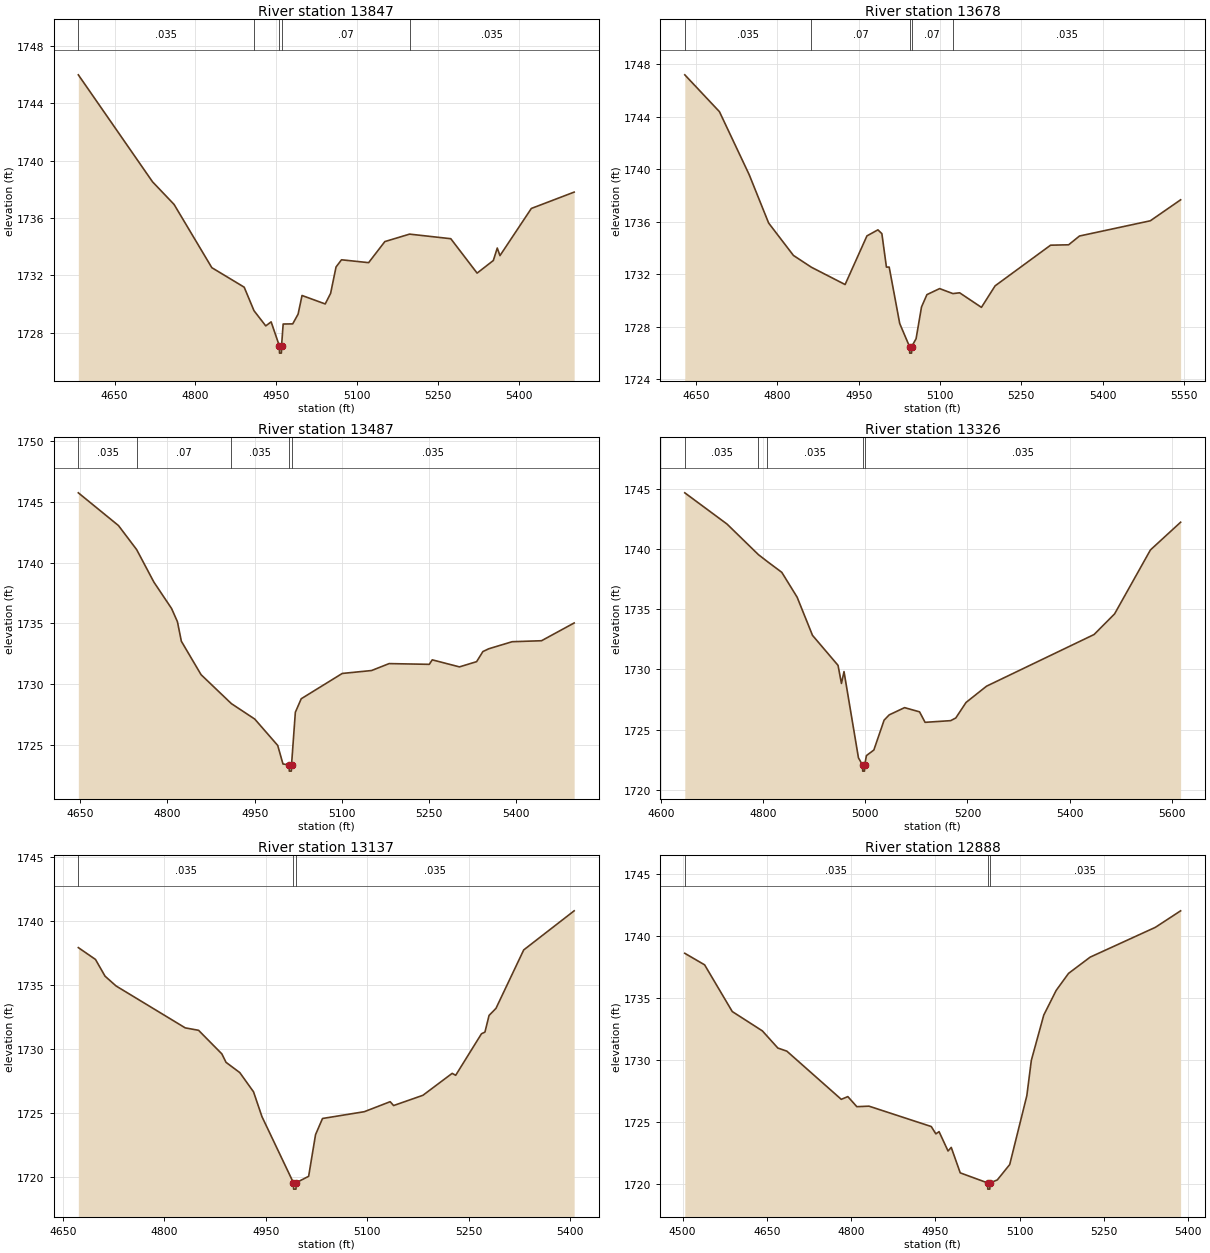
Type RM Length L Ch R = 1,13847,169,169,169
BEGIN DESCRIPTION:
Chimney Creek 1167 26.0
END DESCRIPTION:
XS GIS Cut Line= 3
      1686864.07      6988470.41      1686870.63      6988887.56
      1686925.26      6989386.98
#Sta/Elev= 30
  4582.8 1745.99  4720.4 1738.53  4760.4 1736.95  4830.4 1732.54  4890.4 1731.18
  4908.6 1729.54  4930.4 1728.48  4940.4 1728.76  4955.7 1727.08  4955.9 1726.58
  4959.4 1726.58  4959.7 1727.08  4962.7 1728.61  4980.4 1728.62  4990.4 1729.30
  4997.7 1730.60  5040.7 1730.01  5050.7 1730.75  5060.8 1732.59  5070.9 1733.09
  5121.2 1732.89  5151.3 1734.36  5197.2 1734.88  5273.6 1734.56  5322.4 1732.16
  5352.5 1733.04  5359.8 1733.91  5364.8 1733.38  5423.0 1736.67  5502.4 1737.81
#Mann=5,-1,0
  4582.8   0.035       0  4908.6    0.07       0  4955.7    0.07       0
  4959.7    0.07       0  5197.2   0.035       0
Bank Sta=4955.7,4959.7
Exp/Cntr=0.3,0.1

Type RM Length L Ch R = 1,13678,191,191,191
BEGIN DESCRIPTION:
Mapping XS 853974b2
END DESCRIPTION:
XS GIS Cut Line= 3
      1686685.69      6988594.54      1686730.82      6988964.28
      1686782.85      6989503.59
#Sta/Elev= 30
  4629.4 1747.19  4693.3 1744.38  4748.1 1739.58  4784.0 1735.89  4829.7 1733.42
  4862.8 1732.52  4925.0 1731.20  4965.3 1734.91  4985.5 1735.37  4992.8 1735.08
  5001.2 1732.53  5006.3 1732.53  5025.7 1728.23  5043.8 1726.47  5044.1 1725.97
  5047.6 1725.97  5047.8 1726.47  5055.9 1727.07  5065.9 1729.49  5075.9 1730.43
  5099.3 1730.89  5123.8 1730.51  5136.2 1730.57  5176.4 1729.46  5201.6 1731.10
  5303.9 1734.20  5337.2 1734.23  5357.2 1734.90  5487.8 1736.06  5543.7 1737.66
#Mann=5,-1,0
  4629.4   0.035       0  4862.8    0.07       0  5043.8    0.07       0
  5047.8    0.07       0  5123.8   0.035       0
Bank Sta=5043.8,5047.8
Exp/Cntr=0.3,0.1

Type RM Length L Ch R = 1,13487,161,161,161
BEGIN DESCRIPTION:
Mapping XS ff6a499e
END DESCRIPTION:
XS GIS Cut Line= 3
      1686510.33      6988689.94      1686569.36      6989040.67
      1686629.91      6989533.71
#Sta/Elev= 30
  4646.9 1745.73  4715.9 1743.04  4747.2 1741.06  4776.8 1738.39  4807.2 1736.22
  4817.3 1735.13  4824.0 1733.53  4857.9 1730.78  4910.0 1728.40  4950.2 1727.13
  4989.7 1724.96  4998.7 1723.44  5009.4 1723.35  5009.6 1722.85  5013.1 1722.85
  5013.4 1723.35  5020.0 1727.69  5030.1 1728.80  5100.6 1730.88  5151.0 1731.12
  5181.2 1731.69  5250.3 1731.63  5255.3 1732.00  5302.1 1731.42  5331.6 1731.85
  5342.4 1732.68  5352.5 1732.91  5392.8 1733.49  5443.2 1733.57  5499.3 1735.03
#Mann=5,-1,0
  4646.9   0.035       0  4747.2    0.07       0  4910.0   0.035       0
  5009.4   0.035       0  5013.4   0.035       0
Bank Sta=5009.4,5013.4
Exp/Cntr=0.3,0.1

Type RM Length L Ch R = 1,13326,189,189,189
BEGIN DESCRIPTION:
Mapping XS 2a4389fc
END DESCRIPTION:
XS GIS Cut Line= 3
      1686423.53      6988688.28      1686407.91      6989044.14
      1686362.77      6989656.98
#Sta/Elev= 30
  4646.7 1744.65  4729.3 1742.06  4790.8 1739.52  4808.5 1738.94  4836.6 1738.05
  4866.6 1735.99  4896.7 1732.82  4946.7 1730.33  4953.4 1728.83  4958.4 1729.81
  4986.7 1722.65  4994.8 1722.05  4995.0 1721.55  4998.5 1721.55  4998.8 1722.05
  5002.3 1722.84  5016.8 1723.30  5036.9 1725.78  5046.9 1726.22  5077.0 1726.82
  5106.3 1726.47  5117.1 1725.60  5167.2 1725.74  5177.2 1725.96  5197.3 1727.25
  5237.4 1728.60  5448.0 1732.89  5488.1 1734.60  5558.3 1739.91  5617.4 1742.21
#Mann=5,-1,0
  4646.7   0.035       0  4790.8    0.07       0  4808.5   0.035       0
  4994.8   0.035       0  4998.8   0.035       0
Bank Sta=4994.8,4998.8
Exp/Cntr=0.3,0.1

Type RM Length L Ch R = 1,13137,249,249,249
BEGIN DESCRIPTION:
Mapping XS c0c6d71e
END DESCRIPTION:
XS GIS Cut Line= 3
      1686306.70      6988813.12      1686249.40      6989137.37
      1686160.85      6989530.65
#Sta/Elev= 30
  4673.1 1737.93  4698.4 1737.01  4712.6 1735.70  4728.8 1734.94  4831.0 1731.67
  4850.7 1731.48  4885.1 1729.64  4891.3 1728.98  4911.6 1728.18  4931.9 1726.68
  4944.3 1724.75  4990.8 1719.59  4991.1 1719.09  4994.6 1719.09  4994.9 1719.59
  5013.3 1720.09  5023.5 1723.34  5033.8 1724.60  5095.5 1725.13  5133.7 1725.91
  5138.8 1725.61  5182.1 1726.41  5225.3 1728.12  5230.5 1727.97  5268.6 1731.21
  5273.7 1731.34  5279.8 1732.64  5290.0 1733.19  5331.0 1737.75  5405.5 1740.80
#Mann=3,-1,0
  4673.1   0.035       0  4990.8   0.035       0  4994.9   0.035       0
Bank Sta=4990.8,4994.9
Exp/Cntr=0.3,0.1

Type RM Length L Ch R = 1,12888,309,309,309
BEGIN DESCRIPTION:
Mapping XS 0e4af0da
END DESCRIPTION:
XS GIS Cut Line= 3
      1686258.52      6988754.55      1686015.02      6989192.06
      1685837.93      6989530.63
#Sta/Elev= 30
  4503.9 1738.59  4539.2 1737.66  4588.4 1733.90  4642.1 1732.34  4669.6 1730.96
  4685.6 1730.71  4782.5 1726.83  4794.2 1727.05  4810.2 1726.24  4831.9 1726.28
  4942.7 1724.64  4950.9 1724.05  4956.6 1724.23  4972.6 1722.67  4978.3 1722.96
  4994.3 1720.91  5043.1 1720.10  5043.4 1719.60  5047.0 1719.60  5047.2 1720.10
  5060.3 1720.34  5082.4 1721.58  5112.9 1727.13  5120.9 1729.97  5143.0 1733.61
  5165.1 1735.60  5187.1 1736.97  5225.6 1738.28  5341.7 1740.68  5386.7 1742.01
#Mann=3,-1,0
  4503.9   0.035       0  5043.1   0.035       0  5047.2   0.035       0
Bank Sta=5043.1,5047.2
Exp/Cntr=0.3,0.1

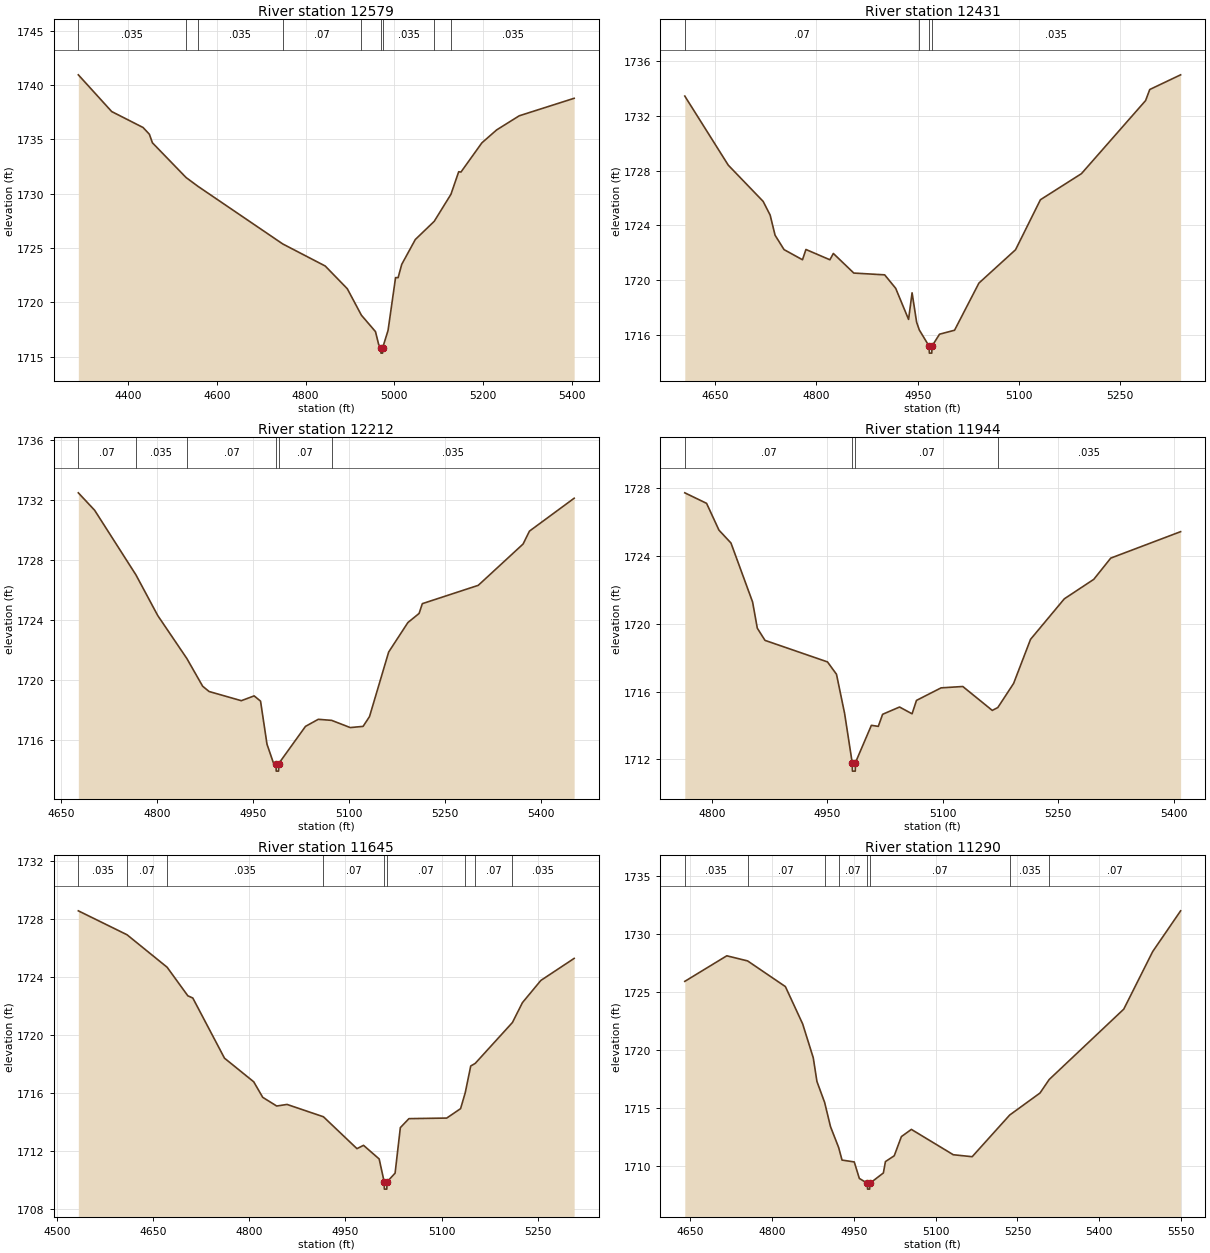
Type RM Length L Ch R = 1,12579,148,148,148
BEGIN DESCRIPTION:
Mapping XS 208d3e65
END DESCRIPTION:
XS GIS Cut Line= 3
      1686241.06      6988567.91      1685746.25      6989087.02
      1685671.59      6989479.43
#Sta/Elev= 30
  4288.3 1740.94  4363.4 1737.56  4434.1 1736.09  4448.3 1735.47  4455.2 1734.68
  4530.8 1731.49  4557.9 1730.67  4748.7 1725.37  4844.3 1723.34  4894.0 1721.25
  4925.8 1718.81  4957.5 1717.30  4964.7 1716.11  4969.6 1715.82  4969.8 1715.32
  4973.4 1715.32  4973.7 1715.82  4985.8 1717.41  5002.7 1722.27  5008.5 1722.27
  5016.6 1723.49  5047.2 1725.78  5089.7 1727.45  5127.4 1729.94  5144.9 1732.02
  5150.0 1731.99  5197.1 1734.68  5230.4 1735.87  5281.3 1737.17  5404.9 1738.78
#Mann=9,-1,0
  4288.3   0.035       0  4530.8    0.07       0  4557.9   0.035       0
  4748.7    0.07       0  4925.8   0.035       0  4969.6   0.035       0
  4973.7   0.035       0  5089.7    0.07       0  5127.4   0.035       0
Bank Sta=4969.6,4973.7
Exp/Cntr=0.3,0.1

Type RM Length L Ch R = 1,12431,219,219,219
BEGIN DESCRIPTION:
Mapping XS 26e06c6c
END DESCRIPTION:
XS GIS Cut Line= 3
      1685744.09      6988595.67      1685643.82      6988982.42
      1685591.74      6989313.11
#Sta/Elev= 30
  4605.1 1733.43  4669.5 1728.39  4721.1 1725.75  4731.5 1724.75  4738.8 1723.28
  4752.1 1722.23  4779.4 1721.49  4784.5 1722.24  4820.0 1721.49  4825.1 1721.95
  4855.4 1720.52  4901.1 1720.39  4917.4 1719.41  4936.5 1717.14  4941.7 1719.08
  4948.4 1716.94  4952.4 1716.37  4967.0 1715.18  4967.3 1714.68  4970.9 1714.68
  4971.1 1715.18  4982.3 1716.06  5004.6 1716.35  5040.7 1719.79  5094.9 1722.22
  5131.8 1725.87  5192.5 1727.77  5287.5 1733.10  5293.7 1733.91  5339.4 1734.98
#Mann=4,-1,0
  4605.1    0.07       0  4952.4   0.035       0  4967.0   0.035       0
  4971.1   0.035       0
Bank Sta=4967,4971.1
Exp/Cntr=0.3,0.1

Type RM Length L Ch R = 1,12212,268,268,268
BEGIN DESCRIPTION:
Mapping XS d1ef6c8d
END DESCRIPTION:
XS GIS Cut Line= 3
      1685427.68      6988564.50      1685461.53      6988889.97
      1685479.76      6989337.87
#Sta/Elev= 30
  4677.1 1732.45  4702.6 1731.29  4767.3 1726.98  4801.3 1724.28  4846.8 1721.42
  4871.6 1719.57  4881.7 1719.22  4932.0 1718.61  4952.1 1718.93  4962.1 1718.58
  4972.2 1715.71  4982.2 1714.47  4986.3 1714.42  4986.6 1713.92  4990.3 1713.92
  4990.5 1714.42  5032.4 1716.90  5052.4 1717.37  5073.3 1717.30  5102.4 1716.82
  5122.5 1716.90  5132.5 1717.55  5162.5 1721.85  5192.5 1723.81  5210.1 1724.42
  5215.1 1725.07  5302.6 1726.29  5372.7 1729.04  5382.7 1729.90  5452.6 1732.09
#Mann=6,-1,0
  4677.1    0.07       0  4767.3   0.035       0  4846.8    0.07       0
  4986.3    0.07       0  4990.5    0.07       0  5073.3   0.035       0
Bank Sta=4986.3,4990.5
Exp/Cntr=0.3,0.1

Type RM Length L Ch R = 1,11944,299,299,299
BEGIN DESCRIPTION:
Mapping XS 8a90beec
END DESCRIPTION:
XS GIS Cut Line= 3
      1685107.93      6988665.35      1685220.75      6988871.47
      1685412.82      6989232.82
#Sta/Elev= 30
  4765.0 1727.72  4793.3 1727.10  4809.4 1725.52  4825.0 1724.76  4853.1 1721.28
  4859.2 1719.74  4869.2 1719.02  4950.4 1717.75  4962.1 1717.02  4972.6 1714.72
  4982.5 1711.81  4982.8 1711.31  4986.5 1711.31  4986.7 1711.81  5007.4 1714.01
  5016.4 1713.95  5022.0 1714.66  5044.0 1715.09  5060.3 1714.69  5066.0 1715.48
  5098.0 1716.22  5126.2 1716.30  5164.5 1714.89  5171.7 1715.06  5192.2 1716.48
  5214.2 1719.08  5258.1 1721.47  5296.4 1722.62  5318.4 1723.87  5409.2 1725.43
#Mann=4,-1,0
  4765.0    0.07       0  4982.5    0.07       0  4986.7    0.07       0
  5171.7   0.035       0
Bank Sta=4982.5,4986.7
Exp/Cntr=0.3,0.1

Type RM Length L Ch R = 1,11645,355,355,355
BEGIN DESCRIPTION:
Mapping XS a68f43fd
END DESCRIPTION:
XS GIS Cut Line= 3
      1684705.34      6988906.19      1685114.42      6989130.80
      1685380.00      6989283.03
#Sta/Elev= 30
  4533.6 1728.58  4609.5 1726.93  4672.0 1724.69  4704.3 1722.72  4712.0 1722.57
  4761.4 1718.42  4807.0 1716.79  4821.0 1715.72  4842.8 1715.12  4858.9 1715.23
  4915.6 1714.38  4967.9 1712.18  4978.1 1712.41  5002.5 1711.47  5010.3 1709.89
  5010.6 1709.39  5014.4 1709.39  5014.7 1709.89  5027.3 1710.49  5035.5 1713.63
  5048.9 1714.25  5107.8 1714.29  5129.4 1714.94  5136.7 1716.05  5145.2 1717.88
  5152.2 1718.06  5210.2 1720.88  5225.8 1722.25  5254.5 1723.78  5306.4 1725.30
#Mann=9,-1,0
  4533.6   0.035       0  4609.5    0.07       0  4672.0   0.035       0
  4915.6    0.07       0  5010.3    0.07       0  5014.7    0.07       0
  5136.7   0.035       0  5152.2    0.07       0  5210.2   0.035       0
Bank Sta=5010.3,5014.7
Exp/Cntr=0.3,0.1

Type RM Length L Ch R = 1,11290,235,235,235
BEGIN DESCRIPTION:
Mapping XS a394ec4d
END DESCRIPTION:
XS GIS Cut Line= 3
      1684542.07      6989195.45      1684883.22      6989310.04
      1685388.46      6989522.29
#Sta/Elev= 30
  4640.8 1725.93  4717.7 1728.13  4755.8 1727.69  4825.0 1725.48  4856.6 1722.27
  4876.0 1719.36  4882.8 1717.31  4896.8 1715.52  4907.6 1713.43  4922.6 1711.62
  4928.7 1710.55  4951.1 1710.39  4960.4 1708.97  4975.2 1708.55  4975.5 1708.05
  4979.3 1708.05  4979.6 1708.55  5004.4 1709.44  5008.2 1710.42  5024.3 1710.92
  5037.4 1712.57  5055.7 1713.19  5132.4 1711.01  5167.0 1710.84  5235.8 1714.43
  5291.2 1716.32  5308.0 1717.48  5444.6 1723.54  5497.5 1728.49  5548.7 1732.00
#Mann=8,-1,0
  4640.8   0.035       0  4755.8    0.07       0  4896.8   0.035       0
  4922.6    0.07       0  4975.2    0.07       0  4979.6    0.07       0
  5235.8   0.035       0  5308.0    0.07       0
Bank Sta=4975.2,4979.6
Exp/Cntr=0.3,0.1

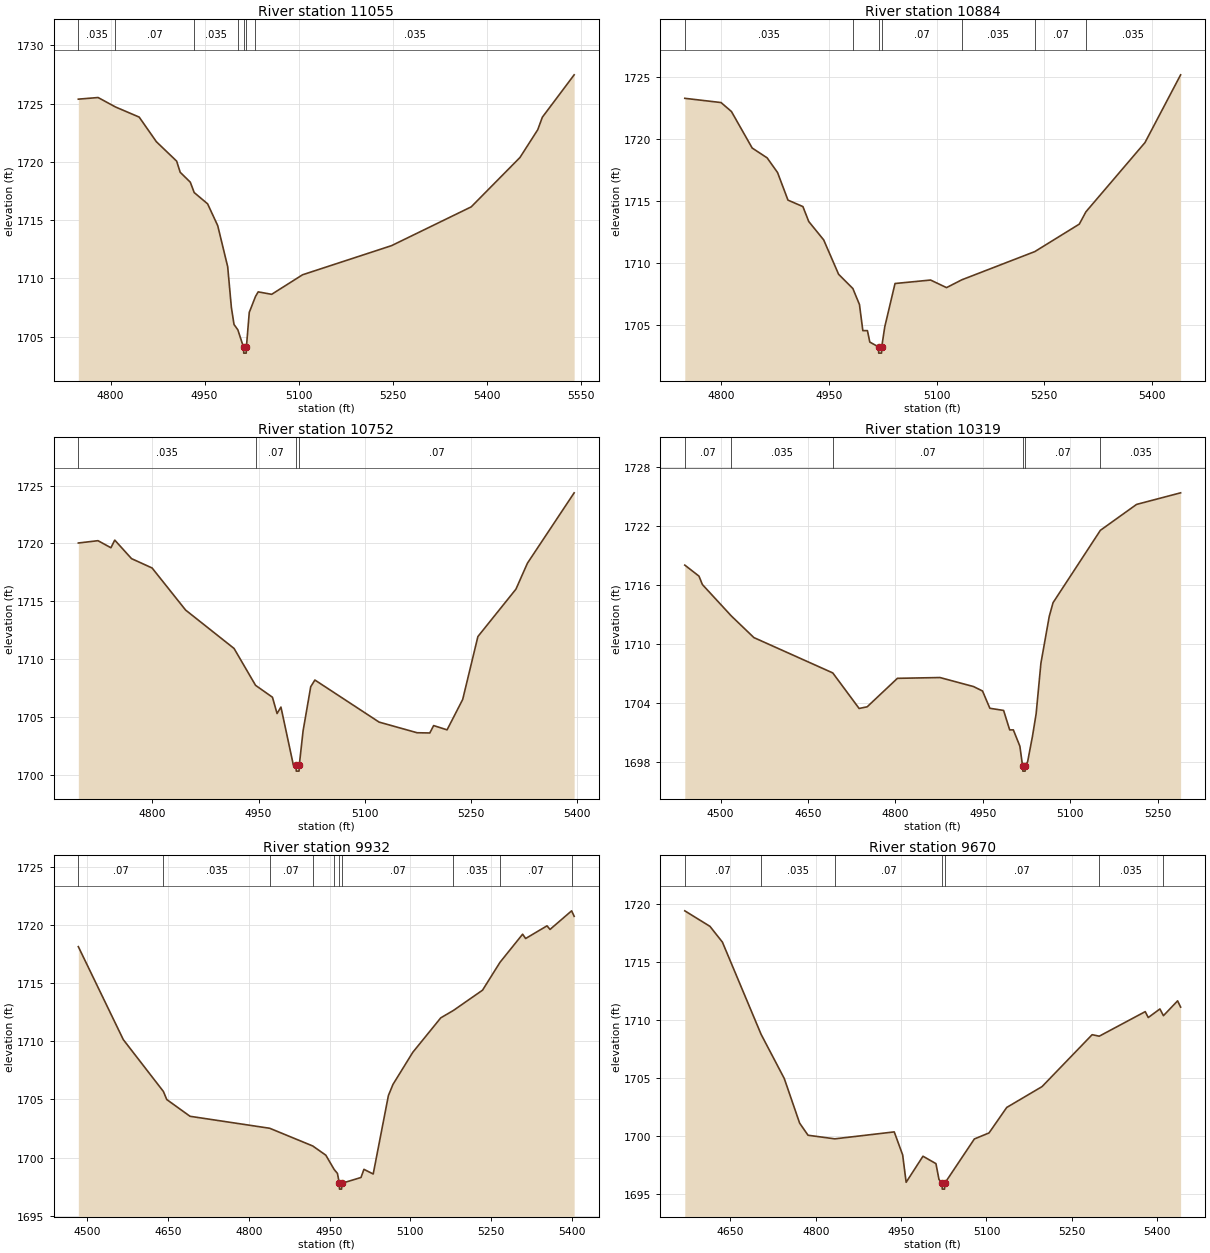
Type RM Length L Ch R = 1,11055,171,171,171
BEGIN DESCRIPTION:
Mapping XS 25d23ad7
END DESCRIPTION:
XS GIS Cut Line= 3
      1684496.08      6989355.83      1684717.43      6989476.92
      1685083.32      6989871.47
#Sta/Elev= 30
  4748.7 1725.39  4780.2 1725.53  4807.9 1724.72  4845.7 1723.85  4873.2 1721.73
  4905.4 1720.07  4911.1 1719.11  4927.2 1718.26  4933.4 1717.37  4954.8 1716.40
  4970.9 1714.53  4986.8 1711.00  4992.7 1707.49  4996.9 1706.04  5003.0 1705.58
  5012.1 1704.08  5012.4 1703.58  5016.3 1703.58  5016.6 1704.08  5021.2 1707.08
  5031.1 1708.44  5035.4 1708.84  5056.9 1708.63  5106.2 1710.31  5248.0 1712.81
  5375.0 1716.14  5452.7 1720.38  5481.0 1722.76  5488.4 1723.84  5539.1 1727.48
#Mann=7,-1,0
  4748.7   0.035       0  4807.9    0.07       0  4933.4   0.035       0
  5003.0    0.07       0  5012.1   0.035       0  5016.6    0.07       0
  5031.1   0.035       0
Bank Sta=5012.1,5016.6
Exp/Cntr=0.3,0.1

Type RM Length L Ch R = 1,10884,132,132,132
BEGIN DESCRIPTION:
Mapping XS d2698146
END DESCRIPTION:
XS GIS Cut Line= 3
      1684441.33      6989400.25      1684595.86      6989598.20
      1684875.35      6989936.70
#Sta/Elev= 30
  4749.6 1723.25  4800.0 1722.91  4814.5 1722.19  4843.4 1719.25  4864.2 1718.46
  4878.7 1717.28  4893.2 1715.06  4914.0 1714.54  4922.1 1713.34  4942.9 1711.86
  4963.7 1709.09  4983.5 1707.95  4992.7 1706.66  4997.4 1704.56  5003.8 1704.56
  5007.1 1703.64  5019.2 1703.25  5019.5 1702.75  5023.4 1702.75  5023.7 1703.25
  5027.9 1704.86  5042.2 1708.35  5091.7 1708.63  5113.9 1708.02  5135.2 1708.65
  5236.8 1710.92  5298.7 1713.13  5307.9 1714.12  5390.1 1719.69  5439.7 1725.14
#Mann=7,-1,0
  4749.6   0.035       0  4983.5    0.07       0  5019.2    0.07       0
  5023.7    0.07       0  5135.2   0.035       0  5236.8    0.07       0
  5307.9   0.035       0
Bank Sta=5019.2,5023.7
Exp/Cntr=0.3,0.1

Type RM Length L Ch R = 1,10752,433,433,433
BEGIN DESCRIPTION:
Mapping XS 93147d09
END DESCRIPTION:
XS GIS Cut Line= 3
      1684380.07      6989405.19      1684499.43      6989687.32
      1684644.18      6990054.59
#Sta/Elev= 30
  4695.2 1720.04  4723.0 1720.24  4741.3 1719.63  4746.7 1720.29  4770.4 1718.69
  4799.5 1717.88  4846.9 1714.24  4915.4 1710.92  4945.8 1707.73  4969.7 1706.70
  4976.2 1705.29  4981.7 1705.85  4999.2 1700.85  5003.1 1700.81  5003.4 1700.31
  5007.3 1700.31  5007.6 1700.81  5013.0 1703.79  5023.8 1707.61  5029.7 1708.19
  5120.5 1704.55  5174.2 1703.63  5192.2 1703.61  5197.6 1704.25  5216.6 1703.88
  5238.7 1706.51  5260.2 1711.95  5314.0 1716.05  5330.2 1718.29  5396.3 1724.38
#Mann=4,-1,0
  4695.2   0.035       0  4945.8    0.07       0  5003.1    0.07       0
  5007.6    0.07       0
Bank Sta=5003.1,5007.6
Exp/Cntr=0.3,0.1

Type RM Length L Ch R = 1,10319,387,387,387
BEGIN DESCRIPTION:
Mapping XS 04284387
END DESCRIPTION:
XS GIS Cut Line= 3
      1683951.70      6989668.66      1684426.95      6989967.05
      1684602.76      6990197.11
#Sta/Elev= 30
  4438.6 1718.04  4462.9 1716.92  4468.8 1716.06  4518.3 1712.87  4557.1 1710.66
  4692.5 1707.06  4737.7 1703.44  4751.5 1703.61  4803.4 1706.51  4876.4 1706.59
  4934.1 1705.67  4949.4 1705.22  4962.0 1703.46  4985.6 1703.24  4996.0 1701.26
  5002.3 1701.26  5013.5 1699.60  5018.2 1697.56  5018.6 1697.06  5022.5 1697.06
  5022.8 1697.56  5026.8 1698.02  5035.1 1700.60  5041.4 1702.90  5049.6 1708.05
  5063.9 1712.82  5070.4 1714.21  5151.6 1721.58  5213.7 1724.22  5289.3 1725.40
#Mann=6,-1,0
  4438.6    0.07       0  4518.3   0.035       0  4692.5    0.07       0
  5018.2    0.07       0  5022.8    0.07       0  5151.6   0.035       0
Bank Sta=5018.2,5022.8
Exp/Cntr=0.3,0.1

Type RM Length L Ch R = 1,9932,262,262,262
BEGIN DESCRIPTION:
Mapping XS e1d29581
END DESCRIPTION:
XS GIS Cut Line= 3
      1683635.24      6989852.91      1684084.43      6990108.97
      1684448.36      6990283.35
#Sta/Elev= 30
  4483.6 1718.13  4567.1 1710.14  4641.6 1705.68  4647.8 1704.99  4691.0 1703.55
  4839.0 1702.52  4918.8 1701.00  4943.1 1700.21  4958.6 1698.98  4964.7 1698.64
  4968.2 1697.79  4968.5 1697.29  4972.4 1697.29  4972.8 1697.79  5008.4 1698.29
  5013.9 1698.99  5031.1 1698.59  5059.3 1705.33  5067.8 1706.29  5104.6 1709.05
  5156.5 1712.01  5180.1 1712.65  5234.1 1714.39  5266.6 1716.79  5308.5 1719.20
  5314.1 1718.83  5353.8 1719.92  5359.4 1719.61  5399.5 1721.21  5404.2 1720.74
#Mann=10,-1,0
  4483.6    0.07       0  4641.6   0.035       0  4839.0    0.07       0
  4918.8   0.035       0  4958.6    0.07       0  4968.2    0.07       0
  4972.8    0.07       0  5180.1   0.035       0  5266.6    0.07       0
  5399.5   0.035       0
Bank Sta=4968.2,4972.8
Exp/Cntr=0.3,0.1

Type RM Length L Ch R = 1,9670,302,302,302
BEGIN DESCRIPTION:
Mapping XS 4ad44921
END DESCRIPTION:
XS GIS Cut Line= 3
      1683501.00      6989939.53      1683855.15      6990189.51
      1684268.73      6990333.43
#Sta/Elev= 30
  4569.8 1719.43  4614.0 1718.09  4635.9 1716.73  4703.9 1708.77  4744.6 1704.96
  4771.6 1701.11  4786.4 1700.06  4833.4 1699.75  4937.9 1700.35  4952.7 1698.36
  4958.8 1696.00  4988.4 1698.25  5011.2 1697.61  5016.5 1696.25  5022.0 1695.91
  5022.3 1695.41  5026.3 1695.41  5026.6 1695.91  5078.7 1699.74  5104.5 1700.26
  5135.6 1702.46  5197.7 1704.26  5285.7 1708.74  5298.2 1708.61  5379.0 1710.73
  5384.3 1710.22  5404.8 1710.96  5411.0 1710.38  5435.9 1711.66  5441.2 1711.12
#Mann=7,-1,0
  4569.8    0.07       0  4703.9   0.035       0  4833.4    0.07       0
  5022.0    0.07       0  5026.6    0.07       0  5298.2   0.035       0
  5411.0    0.07       0
Bank Sta=5022,5026.6
Exp/Cntr=0.3,0.1

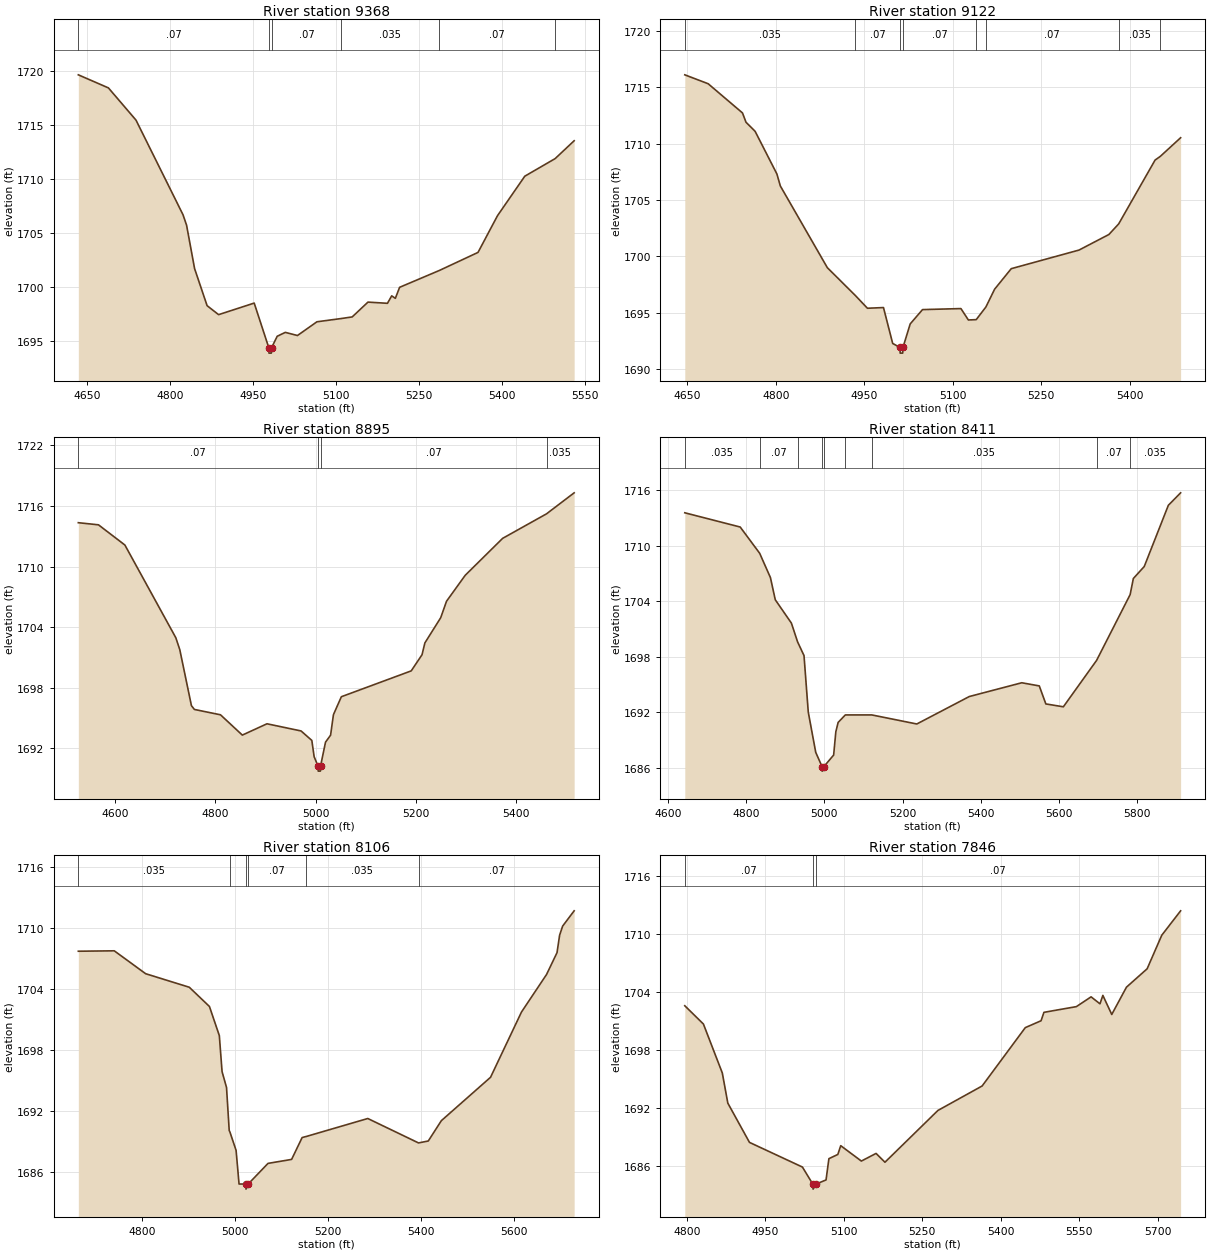
Type RM Length L Ch R = 1,9368,246,246,246
BEGIN DESCRIPTION:
Mapping XS db3ec8cc
END DESCRIPTION:
XS GIS Cut Line= 3
      1683373.39      6989994.22      1683599.94      6990285.87
      1683940.57      6990687.60
#Sta/Elev= 30
  4634.3 1719.64  4688.7 1718.43  4738.5 1715.45  4823.5 1706.69  4829.9 1705.73
  4844.4 1701.71  4867.0 1698.28  4887.8 1697.45  4952.1 1698.52  4978.5 1694.39
  4978.8 1693.89  4983.1 1693.89  4983.5 1694.39  4993.7 1695.45  5008.3 1695.81
  5030.3 1695.52  5065.5 1696.79  5109.3 1697.09  5129.2 1697.24  5157.7 1698.61
  5192.9 1698.50  5200.6 1699.19  5207.2 1698.96  5214.9 1699.98  5286.8 1701.54
  5356.6 1703.21  5391.7 1706.60  5441.1 1710.26  5496.0 1711.89  5530.3 1713.54
#Mann=6,-1,0
  4634.3    0.07       0  4978.5    0.07       0  4983.5    0.07       0
  5109.3   0.035       0  5286.8    0.07       0  5496.0   0.035       0
Bank Sta=4978.5,4983.5
Exp/Cntr=0.3,0.1

Type RM Length L Ch R = 1,9122,227,227,227
BEGIN DESCRIPTION:
Mapping XS 4bcbefd3
END DESCRIPTION:
XS GIS Cut Line= 3
      1683108.00      6990251.48      1683411.40      6990433.79
      1683810.54      6990712.01
#Sta/Elev= 30
  4645.9 1716.11  4685.5 1715.32  4743.7 1712.73  4749.6 1711.91  4765.1 1711.10
  4802.0 1707.32  4807.9 1706.25  4887.5 1699.01  4935.0 1696.54  4955.5 1695.41
  4982.7 1695.47  4998.3 1692.29  5010.6 1691.93  5011.0 1691.43  5015.3 1691.43
  5015.7 1691.93  5028.0 1694.02  5048.9 1695.29  5114.0 1695.38  5126.6 1694.37
  5139.9 1694.40  5156.3 1695.52  5171.1 1697.10  5199.3 1698.92  5314.2 1700.57
  5364.8 1701.95  5381.4 1702.89  5443.1 1708.55  5452.0 1708.88  5486.4 1710.53
#Mann=8,-1,0
  4645.9   0.035       0  4935.0    0.07       0  5010.6    0.07       0
  5015.7    0.07       0  5139.9   0.035       0  5156.3    0.07       0
  5381.4   0.035       0  5452.0    0.07       0
Bank Sta=5010.6,5015.7
Exp/Cntr=0.3,0.1

Type RM Length L Ch R = 1,8895,484,484,484
BEGIN DESCRIPTION:
Mapping XS 1c852e7a
END DESCRIPTION:
XS GIS Cut Line= 3
      1682980.43      6990415.57      1683387.96      6990655.14
      1683835.84      6990912.93
#Sta/Elev= 30
  4526.6 1714.34  4566.8 1714.13  4619.5 1712.13  4721.1 1702.95  4729.1 1701.76
  4752.3 1696.22  4758.2 1695.84  4810.3 1695.31  4853.9 1693.30  4903.1 1694.42
  4971.1 1693.71  4992.6 1692.77  4997.2 1691.16  5004.9 1690.23  5005.3 1689.73
  5009.6 1689.73  5010.0 1690.23  5019.9 1692.60  5030.0 1693.29  5035.7 1695.32
  5051.5 1697.10  5190.9 1699.66  5212.5 1701.26  5218.2 1702.43  5249.8 1704.93
  5261.4 1706.56  5298.7 1709.13  5373.4 1712.79  5461.0 1715.22  5516.1 1717.30
#Mann=4,-1,0
  4526.6    0.07       0  5004.9    0.07       0  5010.0    0.07       0
  5461.0   0.035       0
Bank Sta=5004.9,5010
Exp/Cntr=0.3,0.1

Type RM Length L Ch R = 1,8411,305,305,305
BEGIN DESCRIPTION:
Mapping XS 8b3899f0
END DESCRIPTION:
XS GIS Cut Line= 3
      1682887.61      6990543.80      1683015.65      6990873.66
      1683423.65      6991691.83
#Sta/Elev= 30
  4643.2 1713.56  4784.9 1712.02  4834.7 1709.18  4862.2 1706.55  4874.6 1704.15
  4915.9 1701.62  4931.6 1699.60  4948.1 1698.11  4959.0 1691.99  4978.1 1687.64
  4994.1 1686.11  4994.5 1685.61  4999.2 1686.11  5023.9 1687.35  5029.5 1689.87
  5035.4 1690.88  5053.7 1691.69  5121.6 1691.69  5236.6 1690.71  5370.8 1693.68
  5505.0 1695.17  5549.8 1694.83  5566.6 1692.88  5611.4 1692.57  5696.4 1697.59
  5782.2 1704.71  5790.4 1706.45  5818.3 1707.75  5879.9 1714.37  5911.3 1715.72
#Mann=9,-1,0
  4643.2   0.035       0  4834.7    0.07       0  4931.6   0.035       0
  4994.1   0.035       0  4999.2   0.035       0  5053.7    0.07       0
  5121.6   0.035       0  5696.4    0.07       0  5782.2   0.035       0
Bank Sta=4994.1,4999.2
Exp/Cntr=0.3,0.1

Type RM Length L Ch R = 1,8106,260,260,260
BEGIN DESCRIPTION:
Mapping XS b1a9d268
END DESCRIPTION:
XS GIS Cut Line= 3
      1682731.35      6990854.11      1682909.32      6991144.93
      1683224.00      6991800.34
#Sta/Elev= 30
  4662.0 1707.69  4739.4 1707.73  4807.0 1705.48  4901.0 1704.15  4944.4 1702.26
  4965.7 1699.40  4971.6 1695.86  4981.2 1694.30  4987.0 1690.07  4988.7 1689.90
  5001.8 1688.12  5008.2 1684.81  5022.8 1684.81  5023.2 1684.31  5027.9 1684.81
  5070.6 1686.84  5121.4 1687.23  5144.1 1689.38  5152.6 1689.48  5285.5 1691.25
  5394.8 1688.85  5415.8 1689.04  5444.0 1691.04  5549.9 1695.30  5616.5 1701.71
  5670.5 1705.40  5693.1 1707.55  5698.7 1709.27  5705.2 1710.16  5730.0 1711.66
#Mann=6,-1,0
  4662.0   0.035       0  4988.7    0.07       0  5022.8    0.07       0
  5027.9    0.07       0  5152.6   0.035       0  5394.8    0.07       0
Bank Sta=5022.8,5027.9
Exp/Cntr=0.3,0.1

Type RM Length L Ch R = 1,7846,477,477,477
BEGIN DESCRIPTION:
Mapping XS 5c49d9b7
END DESCRIPTION:
XS GIS Cut Line= 3
      1682811.49      6991188.36      1682861.39      6991390.15
      1683186.09      6992054.70
#Sta/Elev= 30
  4796.1 1702.58  4831.7 1700.69  4867.8 1695.63  4878.3 1692.52  4919.7 1688.46
  5020.9 1685.91  5040.9 1684.13  5041.3 1683.63  5046.0 1684.13  5066.0 1684.58
  5071.5 1686.78  5088.5 1687.21  5094.1 1688.12  5133.5 1686.53  5161.6 1687.32
  5178.6 1686.41  5279.8 1691.76  5364.3 1694.29  5446.8 1700.32  5476.9 1701.03
  5482.4 1701.90  5544.4 1702.49  5572.5 1703.50  5589.5 1702.78  5595.0 1703.65
  5612.0 1701.68  5640.1 1704.50  5679.6 1706.40  5707.6 1709.87  5743.6 1712.39
#Mann=3,-1,0
  4796.1    0.07       0  5040.9    0.07       0  5046.0    0.07       0
Bank Sta=5040.9,5046
Exp/Cntr=0.3,0.1

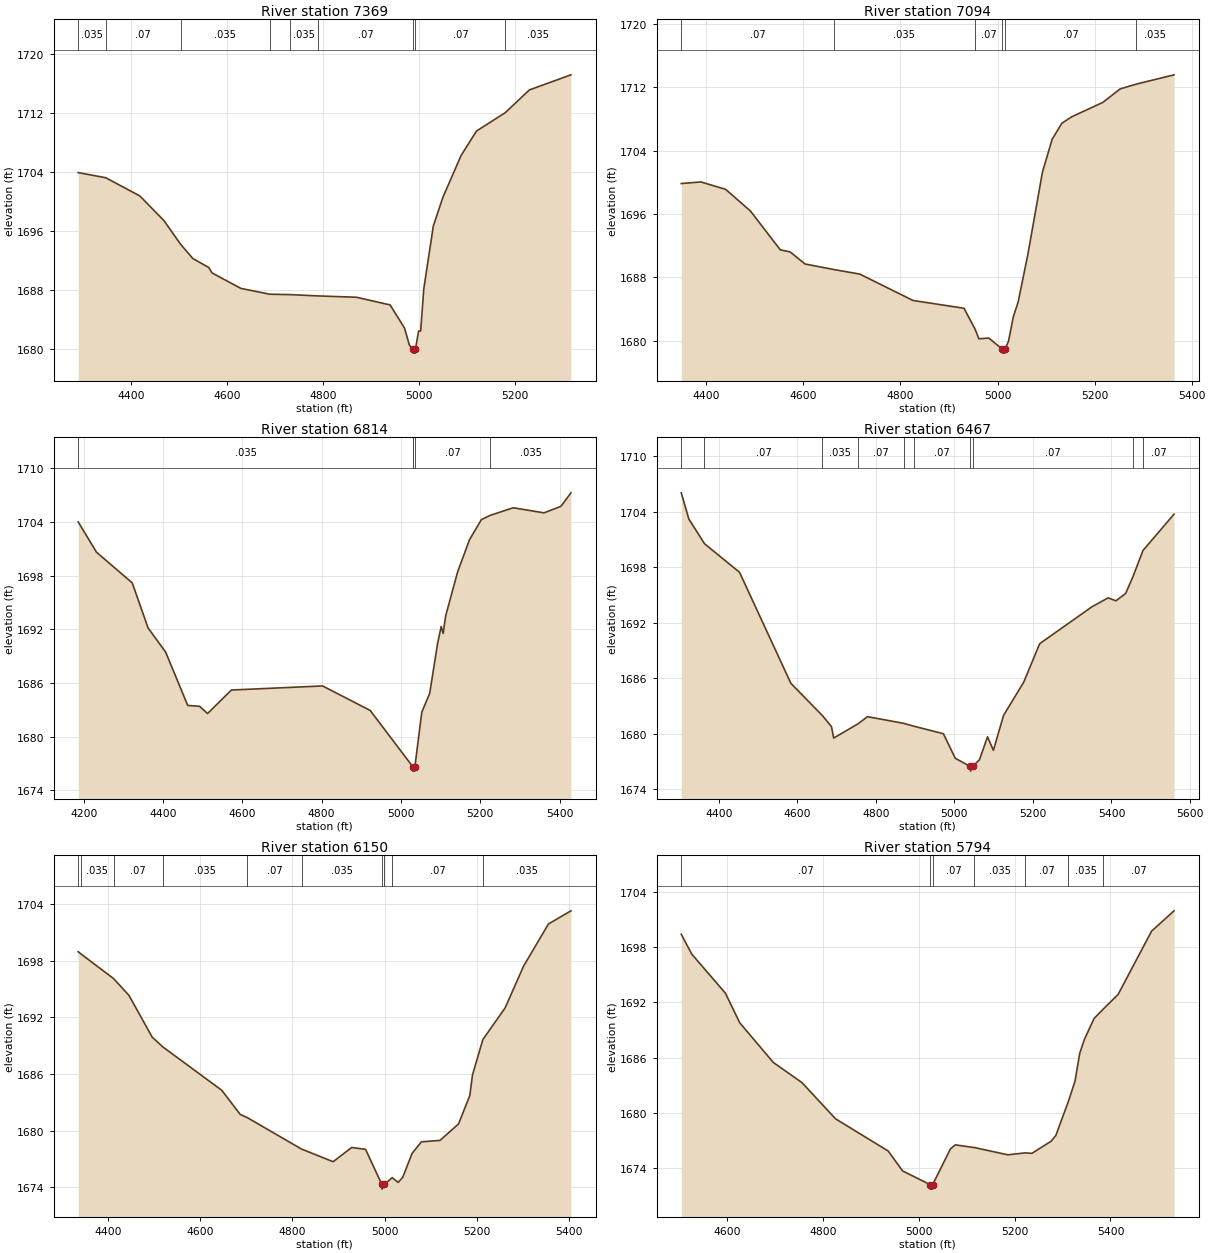
Type RM Length L Ch R = 1,7369,275,275,275
BEGIN DESCRIPTION:
Mapping XS ff0cd00d
END DESCRIPTION:
XS GIS Cut Line= 3
      1682742.22      6991079.83      1682683.62      6991791.63
      1682670.67      6992104.65
#Sta/Elev= 30
  4289.0 1703.91  4346.5 1703.21  4417.6 1700.74  4467.8 1697.40  4502.9 1694.16
  4528.0 1692.26  4561.4 1691.03  4568.1 1690.30  4628.3 1688.20  4688.5 1687.41
  4729.8 1687.36  4788.8 1687.18  4869.1 1687.00  4939.4 1685.96  4969.5 1682.82
  4979.5 1680.54  4986.8 1679.92  4987.3 1679.42  4991.8 1679.42  4992.2 1679.92
  4998.9 1682.42  5003.2 1682.42  5009.6 1688.12  5029.6 1696.68  5049.6 1700.57
  5087.7 1706.26  5119.7 1709.55  5179.6 1712.04  5229.8 1715.12  5316.5 1717.17
#Mann=9,-1,0
  4289.0   0.035       0  4346.5    0.07       0  4502.9   0.035       0
  4688.5    0.07       0  4729.8   0.035       0  4788.8    0.07       0
  4986.8    0.07       0  4992.2    0.07       0  5179.6   0.035       0
Bank Sta=4986.8,4992.2
Exp/Cntr=0.3,0.1

Type RM Length L Ch R = 1,7094,280,280,280
BEGIN DESCRIPTION:
Mapping XS 5dfd507c
END DESCRIPTION:
XS GIS Cut Line= 3
      1682581.44      6991038.63      1682442.56      6991680.95
      1682438.21      6992039.06
#Sta/Elev= 30
  4348.4 1699.84  4388.7 1700.04  4439.8 1699.11  4491.0 1696.37  4552.4 1691.48
  4572.8 1691.21  4603.5 1689.69  4662.2 1689.00  4716.1 1688.42  4825.9 1685.09
  4930.9 1684.11  4953.6 1681.50  4961.6 1680.26  4982.1 1680.35  5009.9 1678.95
  5010.4 1678.45  5014.9 1678.45  5015.3 1678.95  5022.6 1679.94  5032.6 1683.04
  5042.6 1684.92  5062.6 1690.93  5092.6 1701.29  5112.6 1705.43  5132.6 1707.44
  5152.6 1708.25  5217.0 1710.07  5252.6 1711.77  5286.2 1712.38  5363.7 1713.55
#Mann=6,-1,0
  4348.4    0.07       0  4662.2   0.035       0  4953.6    0.07       0
  5009.9    0.07       0  5015.3    0.07       0  5286.2   0.035       0
Bank Sta=5009.9,5015.3
Exp/Cntr=0.3,0.1

Type RM Length L Ch R = 1,6814,347,347,347
BEGIN DESCRIPTION:
Mapping XS d9f14029
END DESCRIPTION:
XS GIS Cut Line= 3
      1682236.39      6990721.79      1682212.52      6991544.23
      1682245.07      6991963.08
#Sta/Elev= 30
  4185.8 1704.02  4232.0 1700.63  4322.1 1697.20  4362.1 1692.16  4406.6 1689.44
  4462.1 1683.49  4492.1 1683.39  4512.1 1682.58  4572.2 1685.21  4802.3 1685.67
  4922.3 1682.93  5029.6 1676.65  5029.7 1676.64  5030.1 1676.14  5034.7 1676.14
  5035.1 1676.64  5052.5 1682.73  5072.5 1684.85  5092.6 1690.48  5101.4 1692.32
  5106.4 1691.54  5112.7 1693.50  5142.8 1698.41  5172.8 1702.02  5202.9 1704.28
  5225.2 1704.75  5283.2 1705.60  5360.8 1705.03  5403.5 1705.76  5428.7 1707.27
#Mann=5,-1,0
  4185.8   0.035       0  5029.6    0.07       0  5029.7   0.035       0
  5035.1    0.07       0  5225.2   0.035       0
Bank Sta=5029.7,5035.1
Exp/Cntr=0.3,0.1

Type RM Length L Ch R = 1,6467,317,317,317
BEGIN DESCRIPTION:
Mapping XS c039db67
END DESCRIPTION:
XS GIS Cut Line= 3
      1682043.25      6990702.22      1681910.87      6991392.32
      1682025.90      6991932.73
#Sta/Elev= 30
  4304.2 1706.02  4323.4 1703.20  4363.3 1700.53  4452.6 1697.44  4583.4 1685.45
  4663.9 1681.96  4686.8 1680.78  4692.5 1679.54  4754.8 1681.09  4778.5 1681.85
  4870.9 1681.13  4897.6 1680.81  4971.9 1680.01  5002.1 1677.36  5040.6 1676.47
  5041.1 1675.97  5046.1 1676.47  5063.8 1677.20  5084.3 1679.68  5099.2 1678.22
  5125.2 1681.99  5176.3 1685.56  5217.2 1689.73  5350.1 1693.71  5391.5 1694.68
  5411.4 1694.36  5436.0 1695.15  5454.7 1696.96  5480.2 1699.79  5559.4 1703.72
#Mann=10,-1,0
  4304.2   0.035       0  4363.3    0.07       0  4663.9   0.035       0
  4754.8    0.07       0  4870.9   0.035       0  4897.6    0.07       0
  5040.6    0.07       0  5046.1    0.07       0  5454.7   0.035       0
  5480.2    0.07       0
Bank Sta=5040.6,5046.1
Exp/Cntr=0.3,0.1

Type RM Length L Ch R = 1,6150,356,356,356
BEGIN DESCRIPTION:
Mapping XS 0d9aa1a8
END DESCRIPTION:
XS GIS Cut Line= 3
      1681709.04      6990578.57      1681641.77      6991238.24
      1681594.03      6991639.72
#Sta/Elev= 30
  4335.9 1698.97  4342.1 1698.73  4412.6 1696.12  4445.9 1694.34  4496.2 1689.91
  4519.3 1688.87  4646.9 1684.27  4687.1 1681.70  4702.2 1681.37  4819.8 1678.03
  4888.2 1676.69  4928.4 1678.20  4958.5 1678.00  4993.6 1674.28  4994.1 1673.78
  4999.1 1674.28  5016.0 1675.00  5029.0 1674.49  5039.0 1675.04  5059.2 1677.57
  5079.3 1678.80  5119.6 1678.95  5159.9 1680.70  5184.2 1683.71  5190.1 1685.91
  5212.5 1689.65  5260.6 1693.00  5300.9 1697.46  5354.5 1701.91  5403.3 1703.31
#Mann=10,-1,0
  4335.9    0.07       0  4342.1   0.035       0  4412.6    0.07       0
  4519.3   0.035       0  4702.2    0.07       0  4819.8   0.035       0
  4993.6   0.035       0  4999.1   0.035       0  5016.0    0.07       0
  5212.5   0.035       0
Bank Sta=4993.6,4999.1
Exp/Cntr=0.3,0.1

Type RM Length L Ch R = 1,5794,231,231,231
BEGIN DESCRIPTION:
Mapping XS 8729d33a
END DESCRIPTION:
XS GIS Cut Line= 3
      1681348.80      6990545.94      1681359.66      6991047.27
      1681357.49      6991574.92
#Sta/Elev= 30
  4503.6 1699.40  4525.7 1697.23  4595.7 1693.00  4625.7 1689.78  4695.7 1685.47
  4755.7 1683.27  4825.7 1679.34  4935.8 1675.83  4965.8 1673.67  5022.9 1672.19
  5023.3 1671.69  5028.2 1671.69  5028.7 1672.19  5065.8 1676.07  5075.8 1676.50
  5115.8 1676.21  5185.8 1675.42  5221.2 1675.63  5235.8 1675.58  5275.8 1676.89
  5285.8 1677.52  5312.1 1681.23  5325.8 1683.41  5335.8 1686.47  5345.8 1688.01
  5365.8 1690.25  5383.6 1691.20  5415.8 1692.85  5485.8 1699.74  5532.7 1701.95
#Mann=7,-1,0
  4503.6    0.07       0  5022.9    0.07       0  5028.7    0.07       0
  5115.8   0.035       0  5221.2    0.07       0  5312.1   0.035       0
  5383.6    0.07       0
Bank Sta=5022.9,5028.7
Exp/Cntr=0.3,0.1