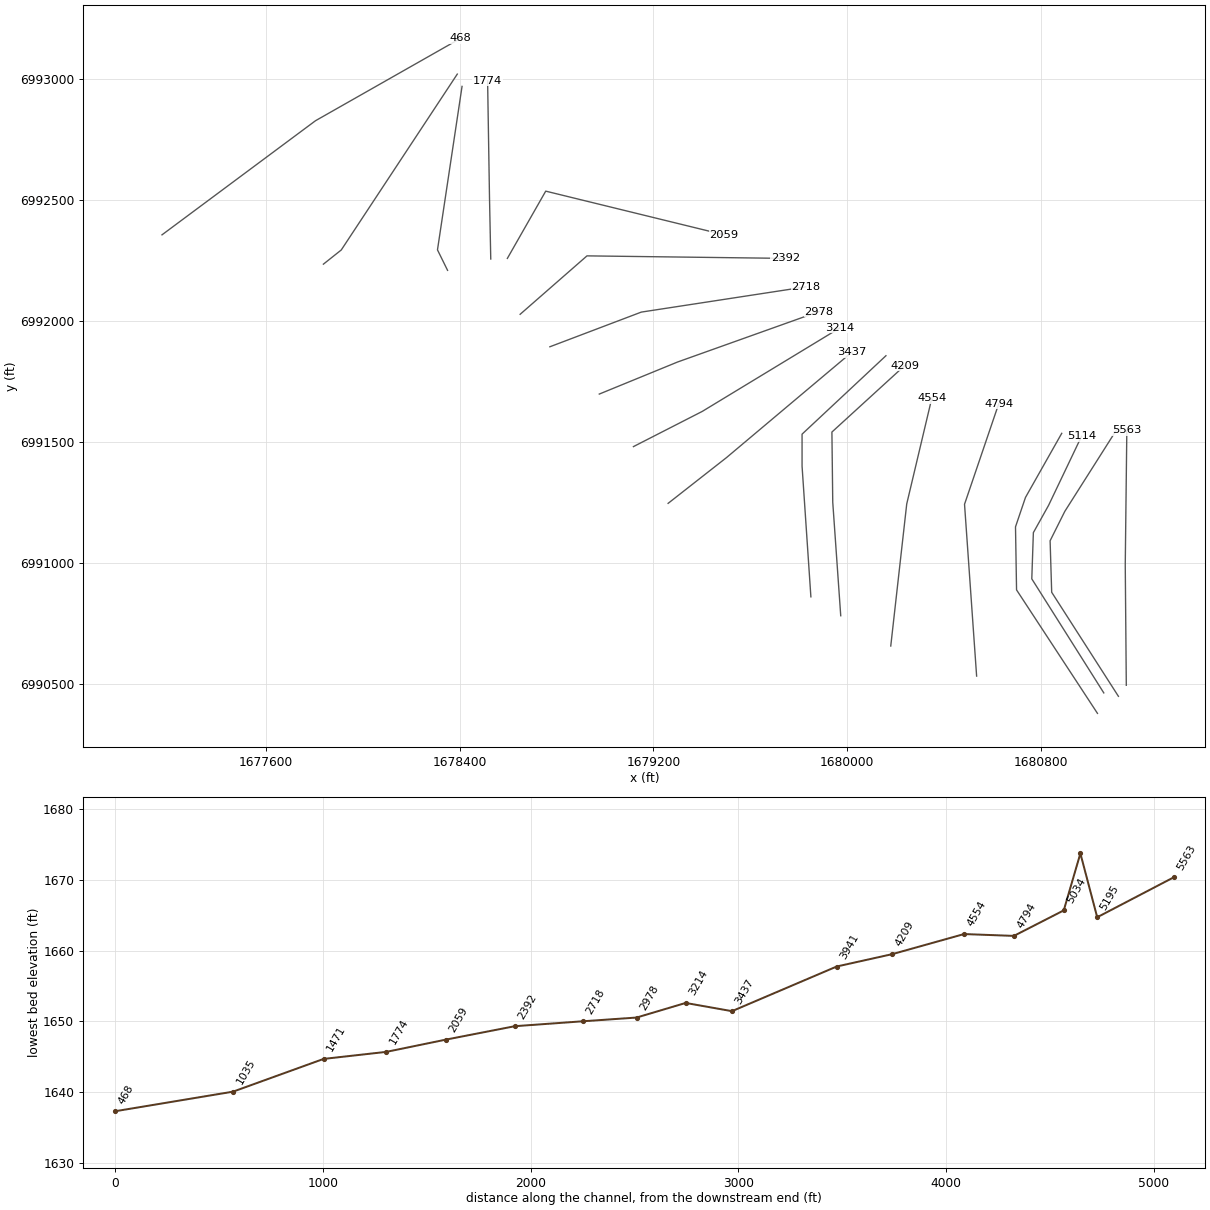
HEC-RAS study Chimney Creek 1167.prj: Chimney Creek 1167 Base Level Engineering

--- Chimney Creek 1167.g01 (geometry) --- (continued)

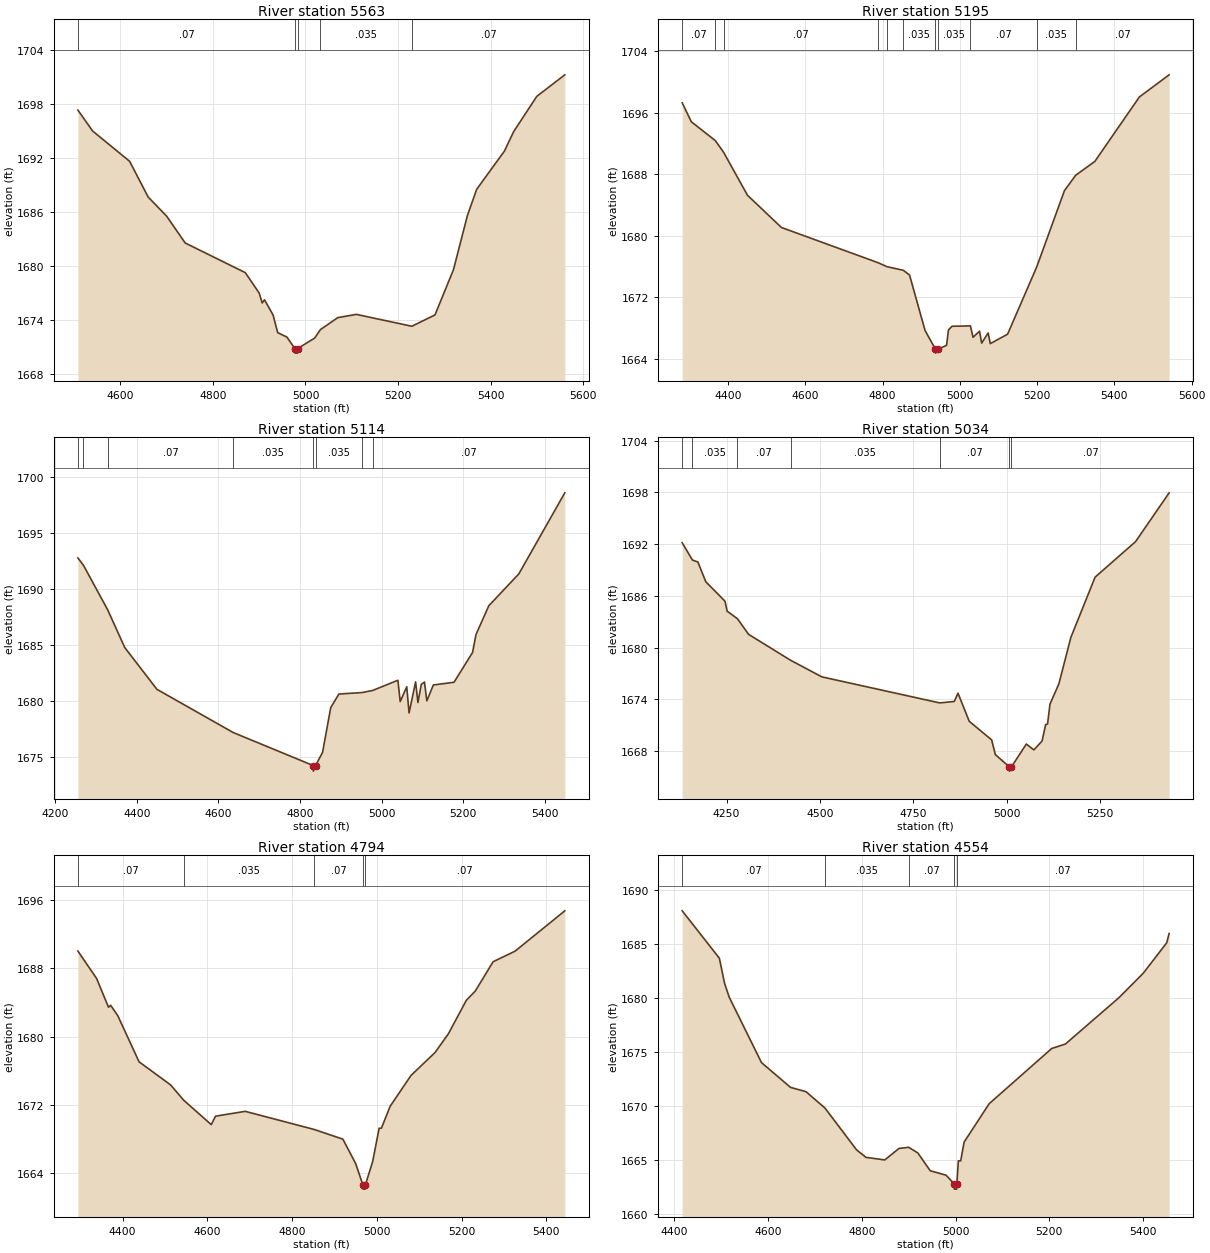
Type RM Length L Ch R = 1,5563,368,368,368
BEGIN DESCRIPTION:
Mapping XS 323119a6
END DESCRIPTION:
XS GIS Cut Line= 3
      1681153.49      6990496.09      1681149.15      6990993.02
      1681155.66      6991548.53
#Sta/Elev= 30
  4508.1 1697.36  4540.0 1695.03  4620.0 1691.66  4660.0 1687.69  4700.0 1685.56
  4740.0 1682.58  4870.0 1679.28  4900.0 1677.01  4906.5 1675.91  4911.5 1676.26
  4930.0 1674.57  4940.0 1672.61  4960.0 1672.11  4977.1 1670.83  4977.6 1670.33
  4982.5 1670.33  4982.9 1670.83  5020.0 1672.01  5032.4 1672.95  5070.0 1674.28
  5110.0 1674.64  5229.9 1673.32  5280.0 1674.58  5320.0 1679.62  5350.1 1685.64
  5370.1 1688.55  5430.1 1692.80  5450.1 1694.97  5500.1 1698.89  5560.6 1701.28
#Mann=5,-1,0
  4508.1    0.07       0  4977.1    0.07       0  4982.9    0.07       0
  5032.4   0.035       0  5229.9    0.07       0
Bank Sta=4977.1,4982.9
Exp/Cntr=0.3,0.1

Type RM Length L Ch R = 1,5195,81,81,81
BEGIN DESCRIPTION:
Mapping XS c198327b
END DESCRIPTION:
XS GIS Cut Line= 5
      1681120.94      6990450.48      1680845.33      6990880.17
      1680838.82      6991092.84      1680899.59      6991214.37
      1681114.44      6991552.92
#Sta/Elev= 30
  4281.6 1697.31  4305.1 1694.85  4367.1 1692.40  4388.5 1690.89  4450.5 1685.27
  4538.4 1681.07  4788.6 1676.48  4811.2 1675.97  4853.8 1675.49  4870.0 1674.87
  4910.0 1667.66  4937.0 1665.20  4937.5 1664.70  4942.9 1665.20  4965.7 1665.71
  4970.7 1667.73  4980.0 1668.20  5027.5 1668.25  5034.2 1666.76  5051.0 1667.56
  5056.6 1666.01  5073.3 1667.33  5078.9 1665.94  5123.7 1667.17  5198.9 1675.91
  5270.8 1685.87  5300.0 1687.88  5349.5 1689.68  5464.8 1698.08  5541.7 1700.96
#Mann=11,-1,0
  4281.6    0.07       0  4367.1   0.035       0  4388.5    0.07       0
  4788.6   0.035       0  4811.2    0.07       0  4853.8   0.035       0
  4937.0   0.035       0  4942.9   0.035       0  5027.5    0.07       0
  5198.9   0.035       0  5300.0    0.07       0
Bank Sta=4937,4942.9
Exp/Cntr=0.3,0.1

Type RM Length L Ch R = 1,5114,80,80,80
BEGIN DESCRIPTION:
Mapping XS e528b189
END DESCRIPTION:
XS GIS Cut Line= 5
      1681060.49      6990464.56      1680763.16      6990935.51
      1680769.67      6991126.49      1680832.60      6991239.33
      1680968.65      6991524.38
#Sta/Elev= 30
  4255.8 1692.76  4269.4 1692.11  4328.9 1688.12  4370.7 1684.75  4449.5 1681.02
  4636.3 1677.16  4832.3 1674.21  4832.8 1673.71  4838.2 1674.21  4855.3 1675.39
  4875.3 1679.38  4895.3 1680.60  4951.8 1680.73  4978.2 1680.92  5039.9 1681.83
  5045.6 1679.93  5061.6 1681.25  5067.3 1678.91  5083.3 1681.69  5089.0 1679.84
  5097.2 1681.46  5105.0 1681.67  5110.8 1679.99  5126.8 1681.41  5177.4 1681.65
  5222.8 1684.31  5231.3 1685.92  5262.7 1688.49  5336.3 1691.34  5448.9 1698.58
#Mann=8,-1,0
  4255.8    0.07       0  4269.4   0.035       0  4328.9    0.07       0
  4636.3   0.035       0  4832.3    0.07       0  4838.2   0.035       0
  4951.8   0.035       0  4978.2    0.07       0
Bank Sta=4832.3,4838.2
Exp/Cntr=0.3,0.1

Type RM Length L Ch R = 1,5034,240,240,240
BEGIN DESCRIPTION:
Mapping XS 5f905b95
END DESCRIPTION:
XS GIS Cut Line= 5
      1681034.40      6990379.99      1680700.22      6990889.94
      1680695.88      6991150.36      1680737.12      6991271.89
      1680886.83      6991536.60
#Sta/Elev= 30
  4131.4 1692.15  4158.9 1690.14  4173.4 1689.92  4194.5 1687.63  4245.8 1685.38
  4251.7 1684.21  4279.0 1683.35  4309.0 1681.53  4421.1 1678.53  4505.0 1676.60
  4820.2 1673.58  4859.2 1673.75  4869.2 1674.71  4899.2 1671.45  4959.2 1669.29
  4969.2 1667.58  5006.4 1666.17  5006.9 1665.67  5012.3 1666.17  5051.9 1668.81
  5072.2 1668.13  5094.1 1669.16  5103.6 1671.06  5108.8 1671.14  5115.2 1673.43
  5139.2 1675.81  5171.0 1681.16  5235.9 1688.16  5344.2 1692.28  5434.0 1697.94
#Mann=7,-1,0
  4131.4    0.07       0  4158.9   0.035       0  4279.0    0.07       0
  4421.1   0.035       0  4820.2    0.07       0  5006.4    0.07       0
  5012.3    0.07       0
Bank Sta=5006.4,5012.3
Exp/Cntr=0.3,0.1

Type RM Length L Ch R = 1,4794,240,240,240
BEGIN DESCRIPTION:
Mapping XS f3abb1e5
END DESCRIPTION:
XS GIS Cut Line= 3
      1680535.30      6990533.99      1680485.38      6991243.67
      1680626.45      6991658.19
#Sta/Elev= 30
  4294.4 1690.04  4338.5 1686.83  4366.7 1683.44  4371.7 1683.67  4388.6 1682.45
  4438.8 1677.03  4513.2 1674.32  4544.3 1672.51  4609.2 1669.65  4619.2 1670.64
  4689.4 1671.21  4852.1 1669.08  4919.9 1667.94  4950.0 1665.08  4967.1 1662.57
  4967.6 1662.07  4972.5 1662.07  4973.0 1662.57  4990.1 1665.30  5005.5 1669.23
  5010.8 1669.23  5031.5 1671.81  5080.7 1675.43  5137.2 1678.11  5168.9 1680.32
  5211.4 1684.27  5232.2 1685.33  5274.5 1688.79  5326.3 1690.03  5443.7 1694.77
#Mann=5,-1,0
  4294.4    0.07       0  4544.3   0.035       0  4852.1    0.07       0
  4967.1    0.07       0  4973.0    0.07       0
Bank Sta=4967.1,4973
Exp/Cntr=0.3,0.1

Type RM Length L Ch R = 1,4554,345,345,345
BEGIN DESCRIPTION:
Mapping XS 98c1c1a4
END DESCRIPTION:
XS GIS Cut Line= 3
      1680180.69      6990658.19      1680246.66      6991244.98
      1680350.28      6991681.88
#Sta/Elev= 30
  4416.5 1688.07  4495.8 1683.69  4506.9 1681.37  4516.9 1680.08  4585.8 1674.03
  4647.8 1671.74  4680.9 1671.34  4721.3 1669.83  4788.6 1665.97  4808.8 1665.27
  4849.0 1665.03  4879.2 1666.09  4899.9 1666.20  4919.5 1665.68  4946.0 1664.03
  4979.8 1663.62  4997.0 1662.83  4997.5 1662.33  5002.4 1662.33  5002.9 1662.83
  5006.0 1664.95  5011.1 1664.95  5018.3 1666.68  5071.8 1670.23  5205.4 1675.34
  5234.6 1675.75  5349.2 1680.05  5400.6 1682.29  5450.8 1685.11  5456.0 1685.97
#Mann=5,-1,0
  4416.5    0.07       0  4721.3   0.035       0  4899.9    0.07       0
  4997.0    0.07       0  5002.9    0.07       0
Bank Sta=4997,5002.9
Exp/Cntr=0.3,0.1

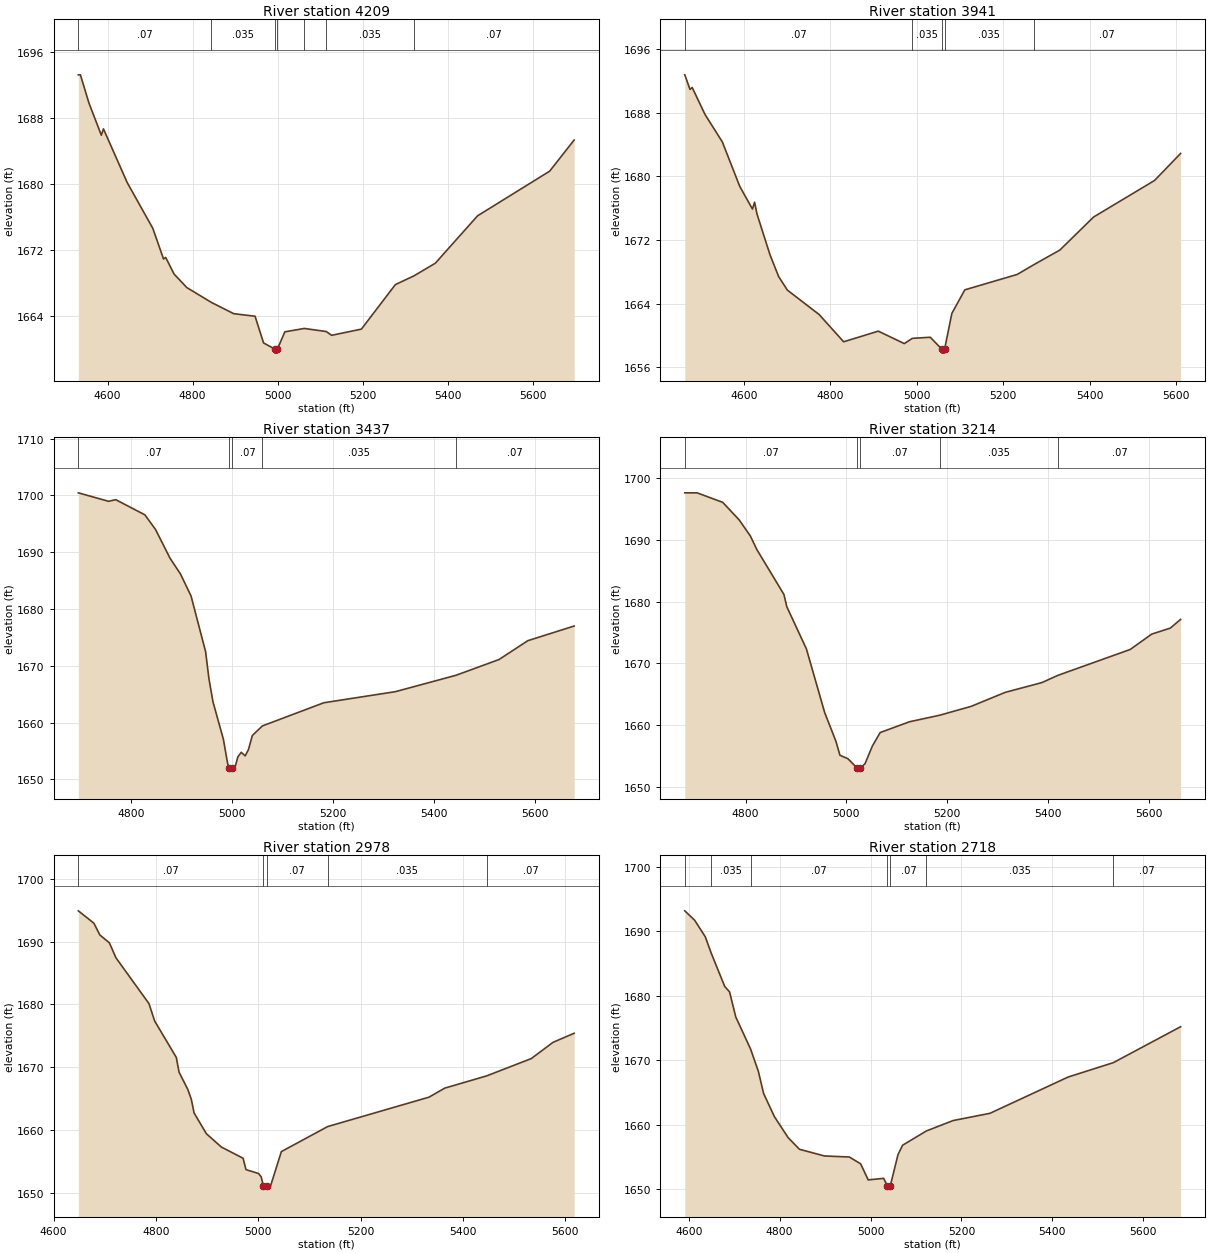
Type RM Length L Ch R = 1,4209,268,268,268
BEGIN DESCRIPTION:
Mapping XS cdeb04bc
END DESCRIPTION:
XS GIS Cut Line= 4
      1679974.09      6990783.22      1679941.11      6991251.92
      1679937.64      6991541.85      1680238.00      6991816.18
#Sta/Elev= 30
  4531.0 1693.23  4535.9 1693.23  4555.8 1689.84  4585.1 1685.91  4590.1 1686.68
  4646.1 1680.16  4706.2 1674.63  4731.5 1670.91  4736.5 1671.10  4756.3 1669.08
  4786.4 1667.44  4844.3 1665.64  4896.7 1664.28  4946.8 1663.97  4966.9 1660.73
  4993.2 1660.00  4993.7 1659.50  4999.0 1659.50  4999.5 1660.00  5016.9 1662.08
  5062.6 1662.49  5114.1 1662.12  5127.0 1661.66  5197.0 1662.41  5277.0 1667.81
  5320.2 1668.85  5371.0 1670.40  5470.3 1676.14  5639.9 1681.55  5697.6 1685.33
#Mann=7,-1,0
  4531.0    0.07       0  4844.3   0.035       0  4993.2   0.035       0
  4999.5   0.035       0  5062.6    0.07       0  5114.1   0.035       0
  5320.2    0.07       0
Bank Sta=4993.2,4999.5
Exp/Cntr=0.3,0.1

Type RM Length L Ch R = 1,3941,504,504,504
BEGIN DESCRIPTION:
Mapping XS 701a386c
END DESCRIPTION:
XS GIS Cut Line= 4
      1679850.83      6990861.25      1679814.37      6991401.23
      1679814.37      6991533.17      1680160.79      6991857.07
#Sta/Elev= 30
  4463.2 1692.80  4475.3 1690.96  4480.3 1691.20  4510.1 1687.80  4550.1 1684.35
  4590.2 1678.77  4619.7 1675.90  4624.7 1676.76  4630.3 1675.27  4660.4 1670.13
  4680.4 1667.39  4700.5 1665.69  4774.1 1662.61  4830.8 1659.18  4911.0 1660.52
  4971.1 1658.95  4989.7 1659.61  5031.2 1659.75  5058.0 1658.25  5058.5 1657.75
  5063.9 1657.75  5064.4 1658.25  5081.2 1662.75  5111.2 1665.72  5232.4 1667.66
  5270.7 1668.88  5331.1 1670.73  5409.2 1674.89  5550.4 1679.50  5610.6 1682.90
#Mann=5,-1,0
  4463.2    0.07       0  4989.7   0.035       0  5058.0   0.035       0
  5064.4   0.035       0  5270.7    0.07       0
Bank Sta=5058,5064.4
Exp/Cntr=0.3,0.1

Type RM Length L Ch R = 1,3437,223,223,223
BEGIN DESCRIPTION:
Mapping XS 00ee792b
END DESCRIPTION:
XS GIS Cut Line= 3
      1679261.20      6991247.39      1679502.05      6991436.17
      1680020.32      6991872.03
#Sta/Elev= 30
  4695.2 1700.45  4755.1 1698.96  4769.5 1699.24  4827.1 1696.58  4848.2 1694.01
  4877.1 1688.93  4897.9 1686.14  4918.7 1682.29  4947.6 1672.48  4954.1 1667.78
  4962.1 1663.69  4982.9 1657.04  4991.0 1652.91  4994.1 1651.95  4994.6 1651.45
  5000.0 1651.45  5000.5 1651.95  5006.4 1652.30  5011.7 1653.99  5018.2 1654.76
  5026.0 1654.14  5032.5 1655.23  5040.3 1657.73  5060.2 1659.41  5182.1 1663.49
  5323.9 1665.44  5444.3 1668.33  5529.4 1671.10  5586.6 1674.42  5678.4 1677.00
#Mann=5,-1,0
  4695.2    0.07       0  4994.1    0.07       0  5000.5    0.07       0
  5060.2   0.035       0  5444.3    0.07       0
Bank Sta=4994.1,5000.5
Exp/Cntr=0.3,0.1

Type RM Length L Ch R = 1,3214,236,236,236
BEGIN DESCRIPTION:
Mapping XS 19a13bfa
END DESCRIPTION:
XS GIS Cut Line= 3
      1679117.95      6991481.74      1679402.23      6991627.14
      1679970.39      6991971.94
#Sta/Elev= 30
  4679.5 1697.56  4704.2 1697.55  4754.8 1696.02  4787.5 1693.18  4809.7 1690.58
  4822.2 1688.44  4876.3 1681.13  4881.9 1679.17  4920.8 1672.36  4957.0 1662.09
  4979.5 1657.41  4987.4 1655.17  5003.3 1654.61  5021.3 1653.11  5021.8 1652.61
  5027.2 1652.61  5027.7 1653.11  5037.1 1653.80  5051.7 1656.66  5067.2 1658.84
  5125.3 1660.58  5185.3 1661.64  5247.7 1663.07  5315.3 1665.33  5388.1 1666.91
  5420.2 1668.09  5563.4 1672.26  5606.0 1674.74  5642.9 1675.71  5663.4 1677.12
#Mann=5,-1,0
  4679.5    0.07       0  5021.3    0.07       0  5027.7    0.07       0
  5185.3   0.035       0  5420.2    0.07       0
Bank Sta=5021.3,5027.7
Exp/Cntr=0.3,0.1

Type RM Length L Ch R = 1,2978,260,260,260
BEGIN DESCRIPTION:
Mapping XS 78d261c6
END DESCRIPTION:
XS GIS Cut Line= 3
      1678976.89      6991698.75      1679300.23      6991831.13
      1679883.98      6992039.46
#Sta/Elev= 30
  4648.2 1694.90  4678.6 1692.93  4690.3 1691.05  4708.9 1689.80  4721.8 1687.41
  4786.3 1680.11  4797.4 1677.34  4839.7 1671.54  4845.1 1669.19  4862.3 1666.42
  4869.1 1664.85  4874.5 1662.68  4898.5 1659.38  4927.9 1657.25  4970.3 1655.47
  4975.9 1653.66  5000.4 1653.04  5005.6 1652.51  5010.0 1651.05  5010.5 1650.55
  5016.5 1651.05  5023.9 1651.05  5045.1 1656.53  5135.6 1660.52  5333.8 1665.21
  5364.6 1666.65  5446.5 1668.60  5533.5 1671.35  5576.0 1673.94  5617.4 1675.39
#Mann=5,-1,0
  4648.2    0.07       0  5010.0    0.07       0  5016.5    0.07       0
  5135.6   0.035       0  5446.5    0.07       0
Bank Sta=5010,5016.5
Exp/Cntr=0.3,0.1

Type RM Length L Ch R = 1,2718,326,326,326
BEGIN DESCRIPTION:
Mapping XS 2db3f4bd
END DESCRIPTION:
XS GIS Cut Line= 3
      1678772.89      6991894.07      1679150.49      6992037.29
      1679829.70      6992141.45
#Sta/Elev= 30
  4591.3 1693.15  4613.0 1691.69  4636.3 1689.14  4649.4 1686.60  4679.1 1681.44
  4689.8 1680.59  4703.5 1676.70  4736.0 1671.74  4753.1 1668.30  4764.7 1664.85
  4788.5 1661.25  4818.7 1658.00  4843.5 1656.20  4898.4 1655.16  4953.3 1655.00
  4978.1 1653.95  4994.9 1651.45  5028.9 1651.69  5036.9 1650.52  5037.4 1650.02
  5042.9 1650.02  5043.4 1650.52  5060.4 1655.37  5070.5 1656.82  5123.0 1659.04
  5181.8 1660.65  5262.8 1661.77  5434.7 1667.39  5534.2 1669.62  5682.3 1675.19
#Mann=7,-1,0
  4591.3    0.07       0  4649.4   0.035       0  4736.0    0.07       0
  5036.9    0.07       0  5043.4    0.07       0  5123.0   0.035       0
  5534.2    0.07       0
Bank Sta=5036.9,5043.4
Exp/Cntr=0.3,0.1

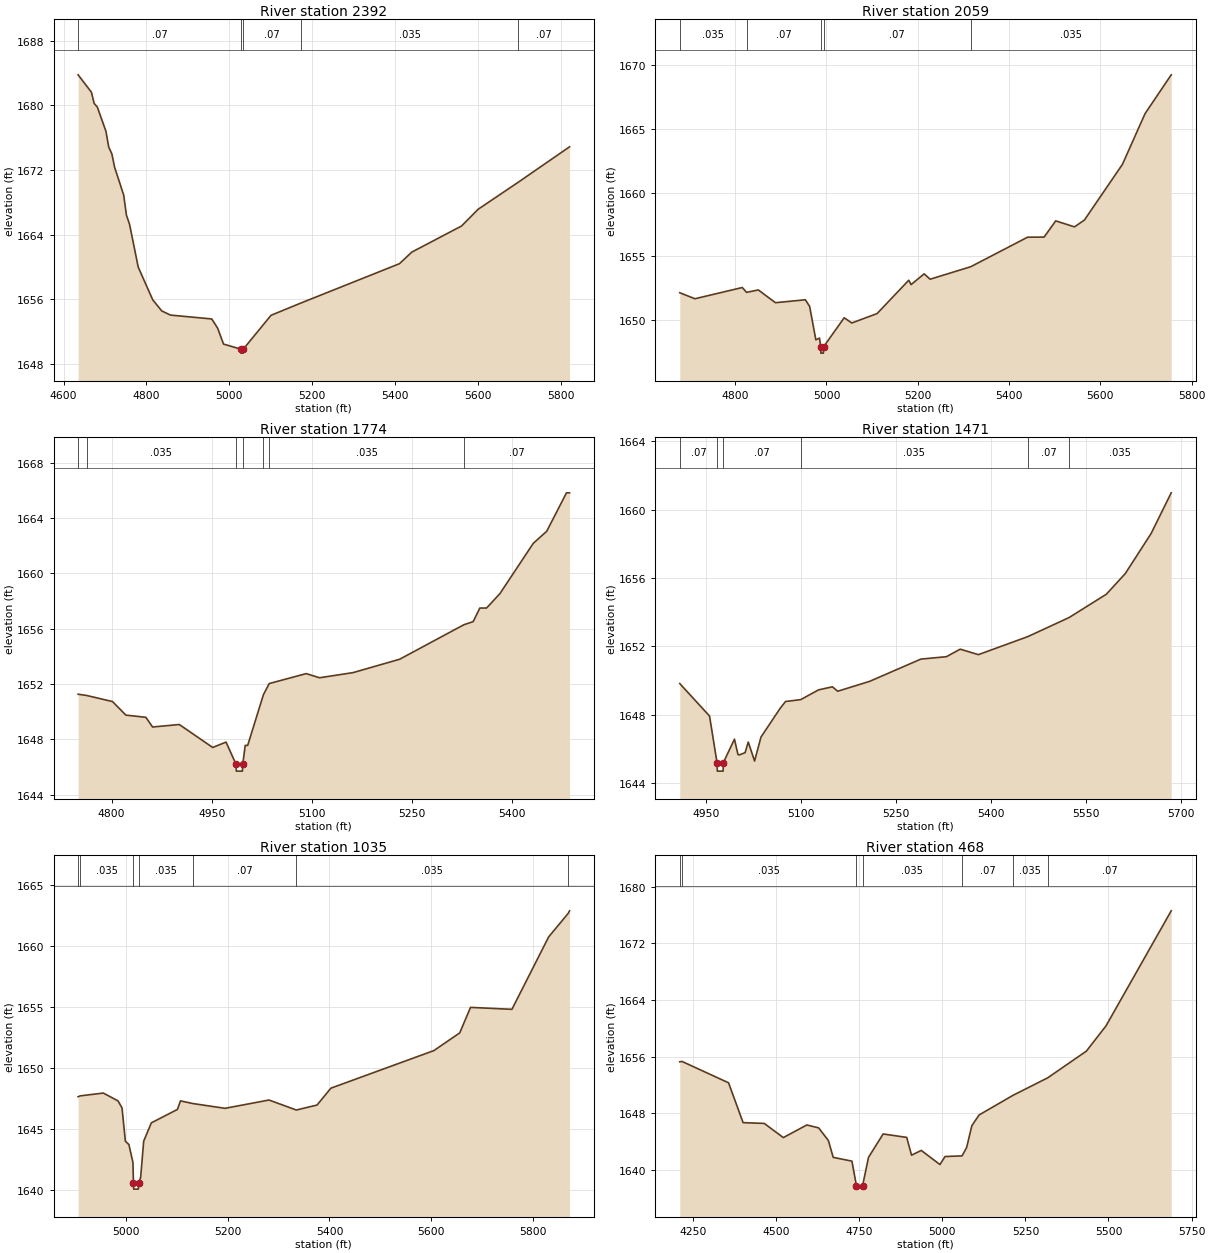
Type RM Length L Ch R = 1,2392,333,333,333
BEGIN DESCRIPTION:
Mapping XS 4136c0a4
END DESCRIPTION:
XS GIS Cut Line= 3
      1678650.04      6992028.17      1678926.10      6992269.50
      1679745.56      6992259.08
#Sta/Elev= 30
  4635.2 1683.78  4667.3 1681.63  4674.0 1680.24  4681.6 1679.79  4702.4 1676.79
  4709.1 1674.84  4716.7 1673.99  4723.3 1672.34  4745.2 1668.90  4751.8 1666.42
  4759.4 1665.27  4780.3 1659.98  4815.4 1655.92  4837.2 1654.55  4858.1 1654.04
  4957.8 1653.56  4972.0 1652.42  4986.2 1650.45  5027.5 1649.83  5028.0 1649.33
  5033.5 1649.33  5034.0 1649.83  5100.8 1654.01  5172.4 1655.52  5410.8 1660.40
  5440.8 1661.84  5560.8 1665.07  5600.8 1667.14  5698.0 1670.50  5821.4 1674.87
#Mann=5,-1,0
  4635.2    0.07       0  5027.5    0.07       0  5034.0    0.07       0
  5172.4   0.035       0  5698.0    0.07       0
Bank Sta=5027.5,5034
Exp/Cntr=0.3,0.1

Type RM Length L Ch R = 1,2059,285,285,285
BEGIN DESCRIPTION:
Mapping XS 93214fef
END DESCRIPTION:
XS GIS Cut Line= 3
      1678597.27      6992259.04      1678755.69      6992536.82
      1679490.70      6992356.86
#Sta/Elev= 30
  4678.7 1652.16  4712.0 1651.69  4815.7 1652.57  4825.0 1652.19  4850.8 1652.38
  4888.3 1651.38  4953.8 1651.61  4963.2 1651.09  4976.8 1648.47  4984.8 1648.61
  4987.3 1647.93  4987.8 1647.43  4993.3 1647.43  4993.8 1647.93  5038.9 1650.20
  5055.5 1649.79  5111.0 1650.53  5180.3 1653.14  5185.5 1652.80  5214.0 1653.64
  5227.1 1653.22  5316.2 1654.20  5440.5 1656.51  5476.8 1656.52  5502.2 1657.79
  5543.4 1657.32  5565.2 1657.86  5648.4 1662.22  5697.9 1666.19  5755.2 1669.23
#Mann=5,-1,0
  4678.7   0.035       0  4825.0    0.07       0  4987.3    0.07       0
  4993.8    0.07       0  5316.2   0.035       0
Bank Sta=4987.3,4993.8
Exp/Cntr=0.3,0.1

Type RM Length L Ch R = 1,1774,303,303,303
BEGIN DESCRIPTION:
Mapping XS 52939c42
END DESCRIPTION:
XS GIS Cut Line= 3
      1678528.69      6992256.56      1678523.48      6992510.45
      1678515.67      6992992.24
#Sta/Elev= 30
  4749.9 1651.27  4762.6 1651.18  4801.4 1650.74  4821.4 1649.76  4851.4 1649.60
  4861.4 1648.90  4901.4 1649.08  4951.4 1647.42  4971.4 1647.81  4986.3 1646.21
  4986.8 1645.71  4995.9 1645.71  4996.4 1646.21  5000.1 1647.57  5003.8 1647.57
  5027.3 1651.23  5036.0 1652.04  5091.4 1652.76  5111.4 1652.46  5161.4 1652.83
  5231.4 1653.80  5327.3 1656.29  5341.4 1656.52  5351.4 1657.50  5361.4 1657.50
  5381.4 1658.54  5431.4 1662.18  5451.5 1663.05  5481.1 1665.83  5485.7 1665.83
#Mann=7,-1,0
  4749.9    0.07       0  4762.6   0.035       0  4986.3   0.035       0
  4996.4   0.035       0  5027.3    0.07       0  5036.0   0.035       0
  5327.3    0.07       0
Bank Sta=4986.3,4996.4
Exp/Cntr=0.3,0.1

Type RM Length L Ch R = 1,1471,436,436,436
BEGIN DESCRIPTION:
Mapping XS d9c95585
END DESCRIPTION:
XS GIS Cut Line= 3
      1678350.29      6992209.70      1678308.64      6992294.30
      1678410.10      6992969.42
#Sta/Elev= 30
  4907.9 1649.83  4955.0 1647.93  4966.8 1645.21  4967.3 1644.71  4976.4 1644.71
  4976.9 1645.21  4994.4 1646.58  4999.9 1645.68  5002.2 1645.66  5011.2 1645.79
  5016.2 1646.41  5026.2 1645.30  5036.3 1646.70  5066.6 1648.38  5075.1 1648.78
  5099.1 1648.89  5127.3 1649.46  5149.2 1649.64  5157.6 1649.38  5208.2 1649.96
  5289.1 1651.26  5329.5 1651.40  5351.3 1651.84  5380.1 1651.52  5458.6 1652.58
  5523.5 1653.69  5582.3 1655.05  5612.3 1656.26  5653.1 1658.60  5684.9 1660.98
#Mann=6,-1,0
  4907.9    0.07       0  4966.8    0.07       0  4976.9    0.07       0
  5099.1   0.035       0  5458.6    0.07       0  5523.5   0.035       0
Bank Sta=4966.8,4976.9
Exp/Cntr=0.3,0.1

Type RM Length L Ch R = 1,1035,567,567,567
BEGIN DESCRIPTION:
Mapping XS dab169b5
END DESCRIPTION:
XS GIS Cut Line= 3
      1677837.49      6992235.26      1677911.29      6992293.87
      1678390.46      6993020.21
#Sta/Elev= 30
  4906.8 1647.66  4910.9 1647.73  4956.2 1647.96  4985.1 1647.32  4993.0 1646.74
  4999.5 1644.02  5006.5 1643.74  5014.4 1642.27  5015.4 1640.59  5015.9 1640.09
  5025.0 1640.09  5025.5 1640.59  5029.5 1641.04  5035.5 1644.02  5050.5 1645.52
  5101.7 1646.62  5107.7 1647.32  5132.2 1647.10  5195.1 1646.71  5281.5 1647.39
  5335.0 1646.57  5375.7 1646.98  5402.8 1648.36  5605.0 1651.44  5655.7 1652.89
  5676.9 1654.98  5758.1 1654.82  5830.3 1660.76  5868.7 1662.69  5871.2 1662.89
#Mann=7,-1,0
  4906.8    0.07       0  4910.9   0.035       0  5015.4   0.035       0
  5025.5   0.035       0  5132.2    0.07       0  5335.0   0.035       0
  5868.7    0.07       0
Bank Sta=5015.4,5025.5
Exp/Cntr=0.3,0.1

Type RM Length L Ch R = 1,468,0,0,0
BEGIN DESCRIPTION:
Chimney Creek 1167 3.0
END DESCRIPTION:
XS GIS Cut Line= 3
      1677170.93      6992356.36      1677805.03      6992827.72
      1678403.96      6993167.91
#Sta/Elev= 30
  4209.9 1655.29  4216.4 1655.35  4356.7 1652.33  4400.5 1646.71  4464.2 1646.60
  4521.5 1644.60  4592.4 1646.38  4627.9 1645.97  4657.1 1644.19  4671.7 1641.81
  4728.0 1641.28  4741.5 1637.83  4742.0 1637.33  4760.1 1637.83  4778.0 1641.82
  4821.9 1645.11  4892.8 1644.63  4907.4 1642.12  4936.6 1642.79  4992.9 1640.80
  5008.2 1641.93  5059.4 1642.02  5073.1 1643.19  5088.9 1646.28  5110.6 1647.79
  5212.6 1650.56  5317.1 1653.03  5433.6 1656.80  5492.7 1660.37  5688.8 1676.59
#Mann=7,-1,0
  4209.9    0.07       0  4216.4   0.035       0  4741.5   0.035       0
  4760.1   0.035       0  5059.4    0.07       0  5212.6   0.035       0
  5317.1    0.07       0
Bank Sta=4741.5,4760.1
Exp/Cntr=0.3,0.1

Chan Stop Cuts=-1