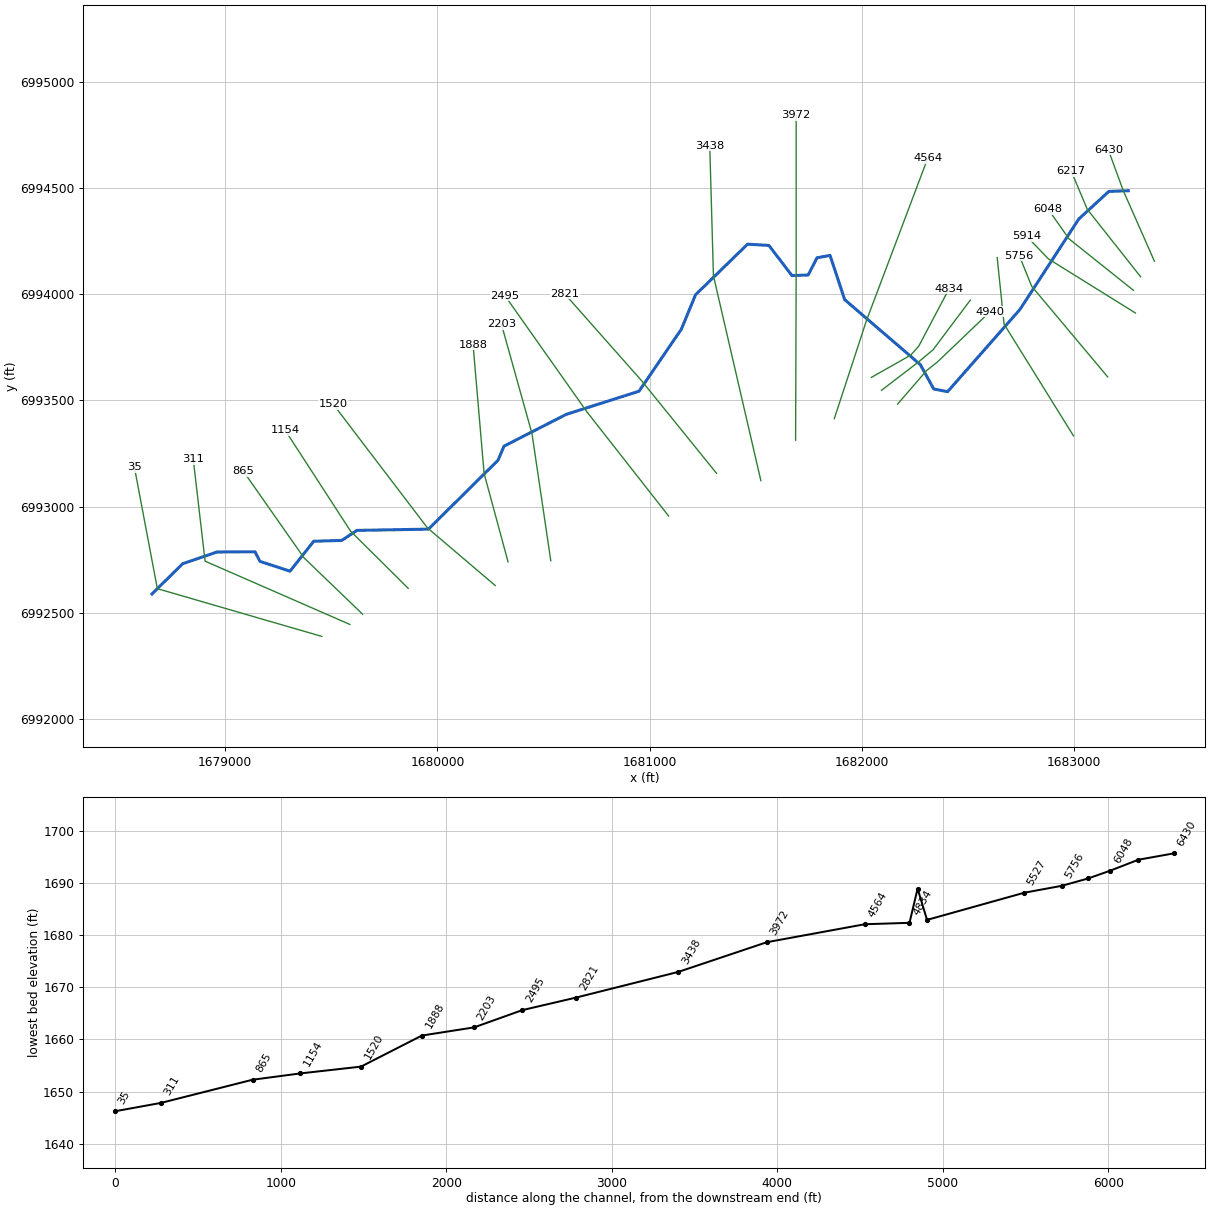
--- Chimney Creek 1168.prj (project) ---

Proj Title=Chimney Creek 1168 Base Level Engineering
Current Plan=p01
Default Exp/Contr=0.3,0.1
English Units
Geom File=g01
Flow File=f01
Plan File=p01
BEGIN DESCRIPTION:
Chimney Creek 1168
END DESCRIPTION:

--- Chimney Creek 1168.p01 (plan) ---

Plan Title=Multiple Run
Short Identifier=Multiple
Geom File=g01
Flow File=f01
Subcritical Flow
K Sum by GR= 0
Std Step Tol= 0.01
Critical Tol= 0.01
Num of Std Step Trials= 20
Max Error Tol= 0.3
Flow Tol Ratio= 0.001
Split Flow NTrial= 30
Split Flow Tol= 0.02
Split Flow Ratio= 0.02
Log Output Level= 0
Friction Slope Method= 1
Unsteady Friction Slope Method= 2
Unsteady Bridges Friction Slope Method= 1
Parabolic Critical Depth
Global Vel Dist=  1 , 1 , 1
Global Log Level= 0
CheckData=True
Encroach Param= -1, 0, 0, 0
BEGIN DESCRIPTION:
Multiple Run
END DESCRIPTION:

--- Chimney Creek 1168.f01 (steady flow) ---

Flow Title=Multiple
Number of Profiles=7
Profile Names=10-year,25-year,50-year,1pct_min,100-year,1pct_plu,500-year
River Rch & RM= Chimney Creek 11,Reach-1,6430
     258     357     438     268     535    1067     807
River Rch & RM= Chimney Creek 11,Reach-1,3972
     324     453     560     345     689    1375    1055
Boundary for River Rch & Prof#=Chimney Creek 11,Reach-1,1
Up Type=0
Dn Type=3
Dn Slope=0.005
Boundary for River Rch & Prof#=Chimney Creek 11,Reach-1,2
Up Type=0
Dn Type=3
Dn Slope=0.005
Boundary for River Rch & Prof#=Chimney Creek 11,Reach-1,3
Up Type=0
Dn Type=3
Dn Slope=0.005
Boundary for River Rch & Prof#=Chimney Creek 11,Reach-1,4
Up Type=0
Dn Type=3
Dn Slope=0.005
Boundary for River Rch & Prof#=Chimney Creek 11,Reach-1,5
Up Type=0
Dn Type=3
Dn Slope=0.005
Boundary for River Rch & Prof#=Chimney Creek 11,Reach-1,6
Up Type=0
Dn Type=3
Dn Slope=0.005
Boundary for River Rch & Prof#=Chimney Creek 11,Reach-1,7
Up Type=0
Dn Type=3
Dn Slope=0.005

--- Chimney Creek 1168.g01 (geometry) ---

Geom Title=Existing Conditions

River Reach=Chimney Creek 11,Reach-1
Reach XY= 30
      1683255.00      6994488.00      1683163.27      6994484.77
      1683021.64      6994354.70      1682744.22      6993928.32
      1682403.32      6993541.08      1682337.95      6993554.05
      1682275.38      6993668.15      1681918.62      6993974.78
      1681849.71      6994183.42      1681788.21      6994171.95
      1681746.65      6994091.00      1681670.22      6994088.13
      1681561.45      6994230.36      1681460.90      6994236.04
      1681215.76      6993997.68      1681149.15      6993835.71
      1680949.53      6993543.26      1680606.58      6993434.17
      1680313.48      6993284.49      1680285.14      6993218.08
      1679957.45      6992893.46      1679620.22      6992887.48
      1679549.05      6992840.28      1679416.83      6992836.36
      1679305.11      6992695.31      1679163.50      6992741.55
      1679140.17      6992786.81      1678960.94      6992785.74
      1678798.83      6992730.14      1678655.00      6992588.00

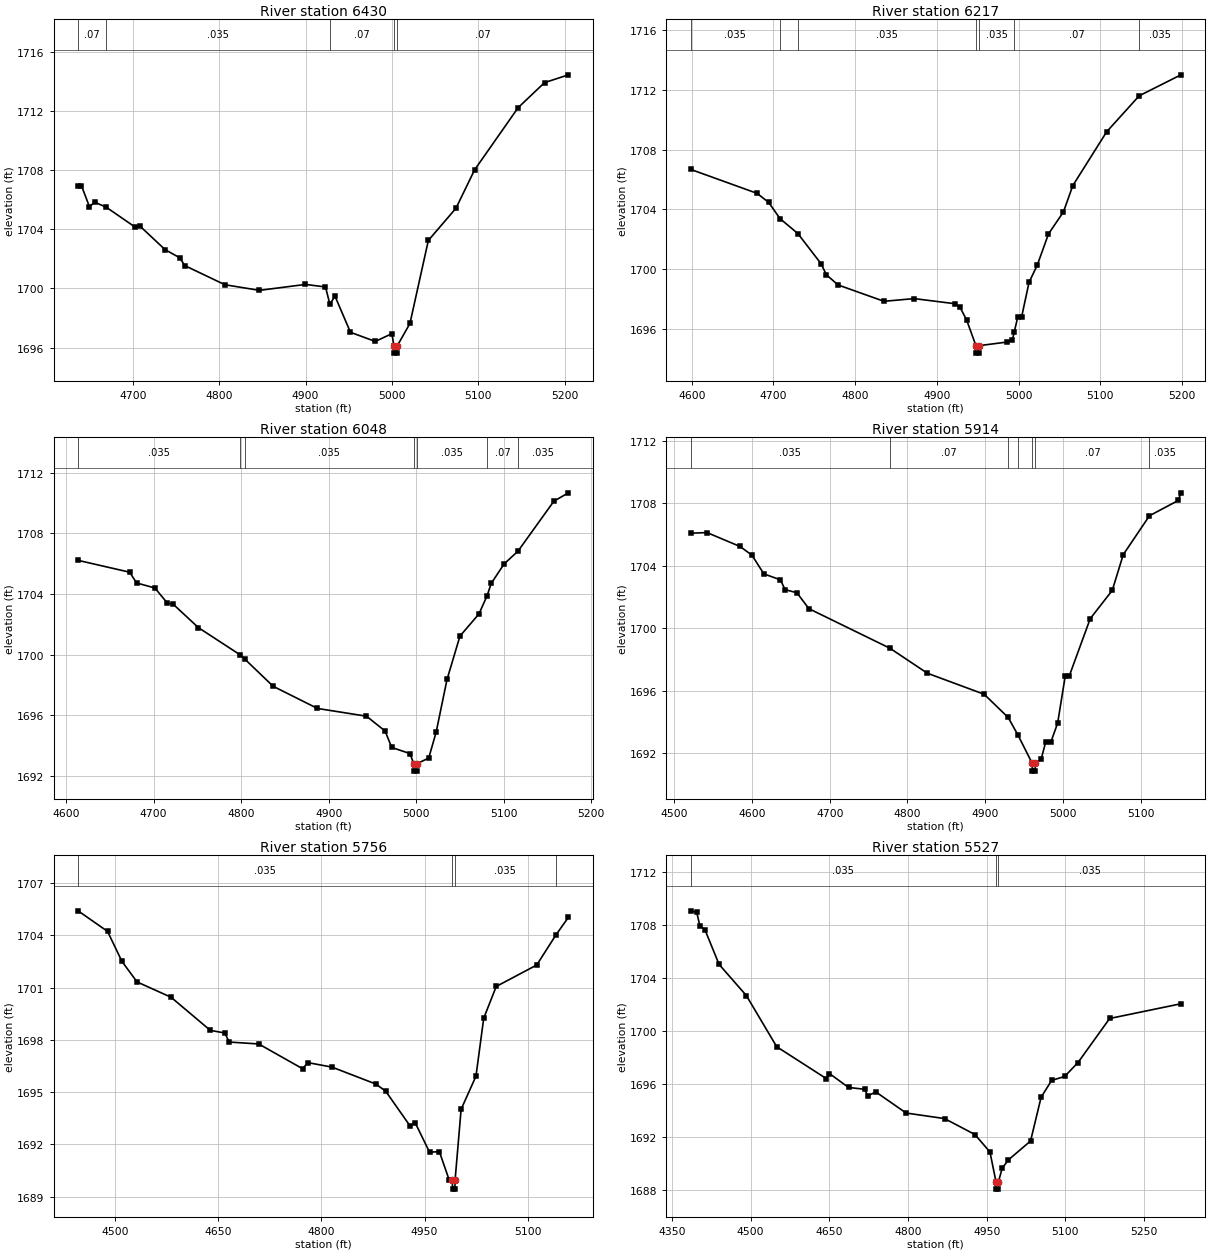
Type RM Length L Ch R = 1,6430,213,213,213
BEGIN DESCRIPTION:
Chimney Creek 1168 12.0
END DESCRIPTION:
XS GIS Cut Line= 3
      1683377.98      6994155.88      1683231.23      6994488.33
      1683160.93      6994680.27
#Sta/Elev= 30
  4636.6 1706.96  4640.5 1706.96  4649.8 1705.53  4655.8 1705.84  4669.2 1705.50
  4702.5 1704.16  4707.9 1704.24  4737.3 1702.63  4754.5 1702.07  4760.0 1701.55
  4806.6 1700.25  4846.6 1699.87  4899.9 1700.27  4923.1 1700.10  4928.2 1698.93
  4934.1 1699.48  4952.0 1697.03  4980.8 1696.41  5000.0 1696.94  5002.3 1696.12
  5002.5 1695.62  5006.0 1695.62  5006.3 1696.12  5020.9 1697.63  5042.2 1703.25
  5074.2 1705.43  5095.8 1708.03  5146.2 1712.24  5176.7 1713.93  5204.4 1714.46
#Mann=5,-1,0
  4636.6    0.07       0  4669.2   0.035       0  4928.2    0.07       0
  5002.3    0.07       0  5006.3    0.07       0
Bank Sta=5002.3,5006.3
Exp/Cntr=0.3,0.1

Type RM Length L Ch R = 1,6217,169,169,169
BEGIN DESCRIPTION:
Mapping XS af6cb1b5
END DESCRIPTION:
XS GIS Cut Line= 3
      1683313.03      6994082.57      1683061.73      6994400.28
      1682986.20      6994579.97
#Sta/Elev= 30
  4598.5 1706.68  4679.8 1705.08  4694.2 1704.47  4708.0 1703.39  4729.9 1702.39
  4758.3 1700.37  4764.7 1699.64  4779.1 1698.96  4835.2 1697.87  4872.1 1698.05
  4921.8 1697.71  4928.2 1697.47  4936.2 1696.64  4947.7 1694.91  4947.9 1694.41
  4951.4 1694.41  4951.7 1694.91  4985.9 1695.15  4992.3 1695.29  4994.7 1695.85
  4998.9 1696.82  5003.6 1696.82  5012.7 1699.14  5022.8 1700.29  5036.5 1702.37
  5054.8 1703.84  5066.2 1705.59  5107.7 1709.19  5147.5 1711.59  5198.5 1712.99
#Mann=7,-1,0
  4598.5   0.035       0  4708.0    0.07       0  4729.9   0.035       0
  4947.7    0.07       0  4951.7   0.035       0  4994.7    0.07       0
  5147.5   0.035       0
Bank Sta=4947.7,4951.7
Exp/Cntr=0.3,0.1

Type RM Length L Ch R = 1,6048,134,134,134
BEGIN DESCRIPTION:
Mapping XS 0545e4c9
END DESCRIPTION:
XS GIS Cut Line= 3
      1683279.18      6994018.76      1682975.79      6994260.96
      1682876.81      6994401.61
#Sta/Elev= 30
  4613.7 1706.22  4672.6 1705.44  4680.6 1704.73  4701.4 1704.40  4715.8 1703.40
  4722.2 1703.34  4751.1 1701.79  4799.2 1699.98  4804.4 1699.70  4836.6 1697.92
  4887.2 1696.46  4943.2 1695.95  4964.5 1694.97  4972.0 1693.89  4992.8 1693.49
  4997.2 1692.83  4997.5 1692.33  5001.0 1692.33  5001.2 1692.83  5014.3 1693.19
  5022.8 1694.90  5035.2 1698.37  5050.0 1701.23  5071.7 1702.69  5081.0 1703.89
  5085.7 1704.70  5100.5 1705.99  5116.2 1706.82  5157.3 1710.12  5173.9 1710.67
#Mann=7,-1,0
  4613.7   0.035       0  4799.2    0.07       0  4804.4   0.035       0
  4997.2   0.035       0  5001.2   0.035       0  5081.0    0.07       0
  5116.2   0.035       0
Bank Sta=4997.2,5001.2
Exp/Cntr=0.3,0.1

Type RM Length L Ch R = 1,5914,158,158,158
BEGIN DESCRIPTION:
Mapping XS 6bf6e797
END DESCRIPTION:
XS GIS Cut Line= 3
      1683288.27      6993912.01      1682878.13      6994167.21
      1682775.76      6994273.47
#Sta/Elev= 30
  4521.0 1706.09  4542.2 1706.13  4584.6 1705.24  4600.0 1704.68  4615.3 1703.48
  4636.6 1703.10  4642.6 1702.47  4657.8 1702.27  4673.2 1701.25  4777.5 1698.71
  4825.5 1697.11  4898.6 1695.76  4929.5 1694.27  4942.0 1693.15  4960.4 1691.33
  4960.6 1690.83  4964.1 1690.83  4964.4 1691.33  4971.8 1691.58  4977.7 1692.69
  4984.2 1692.67  4993.1 1693.91  5002.9 1696.94  5008.1 1696.94  5035.0 1700.61
  5063.3 1702.42  5077.5 1704.72  5111.2 1707.21  5148.2 1708.19  5151.6 1708.68
#Mann=7,-1,0
  4521.0   0.035       0  4777.5    0.07       0  4929.5   0.035       0
  4942.0    0.07       0  4960.4    0.07       0  4964.4    0.07       0
  5111.2   0.035       0
Bank Sta=4960.4,4964.4
Exp/Cntr=0.3,0.1

Type RM Length L Ch R = 1,5756,229,229,229
BEGIN DESCRIPTION:
Mapping XS dcbbb6df
END DESCRIPTION:
XS GIS Cut Line= 3
      1683157.95      6993610.56      1682799.88      6994037.65
      1682741.28      6994182.19
#Sta/Elev= 30
  4446.0 1705.40  4488.9 1704.22  4509.8 1702.50  4531.8 1701.32  4581.3 1700.44
  4638.4 1698.54  4659.4 1698.39  4665.9 1697.87  4708.8 1697.76  4772.6 1696.34
  4780.3 1696.69  4815.5 1696.43  4879.2 1695.46  4893.5 1695.05  4928.7 1693.07
  4936.5 1693.23  4957.3 1691.55  4971.6 1691.58  4985.9 1689.95  4990.4 1689.93
  4990.7 1689.43  4994.2 1689.43  4994.4 1689.93  5003.2 1694.01  5024.8 1695.91
  5036.1 1699.24  5054.3 1701.06  5113.2 1702.29  5140.7 1703.99  5159.3 1705.03
#Mann=4,-1,0
  4446.0   0.035       0  4990.4   0.035       0  4994.4   0.035       0
  5140.7    0.07       0
Bank Sta=4990.4,4994.4
Exp/Cntr=0.3,0.1

Type RM Length L Ch R = 1,5527,587,587,587
BEGIN DESCRIPTION:
Mapping XS 75bd6ceb
END DESCRIPTION:
XS GIS Cut Line= 3
      1682996.51      6993333.19      1682669.67      6993859.26
      1682637.12      6994173.04
#Sta/Elev= 30
  4385.5 1709.08  4397.4 1708.96  4403.3 1707.94  4412.8 1707.67  4439.9 1705.04
  4491.9 1702.69  4549.8 1698.83  4644.2 1696.43  4650.2 1696.81  4686.7 1695.76
  4717.4 1695.62  4723.3 1695.12  4738.7 1695.42  4796.5 1693.83  4869.8 1693.41
  4927.6 1692.21  4956.3 1690.89  4968.1 1688.59  4968.4 1688.09  4971.9 1688.09
  4972.1 1688.59  4979.6 1689.66  4991.6 1690.30  5033.7 1691.72  5053.8 1695.02
  5073.9 1696.29  5098.8 1696.59  5124.2 1697.64  5184.5 1700.96  5320.3 1702.07
#Mann=3,-1,0
  4385.5   0.035       0  4968.1   0.035       0  4972.1   0.035       0
Bank Sta=4968.1,4972.1
Exp/Cntr=0.3,0.1

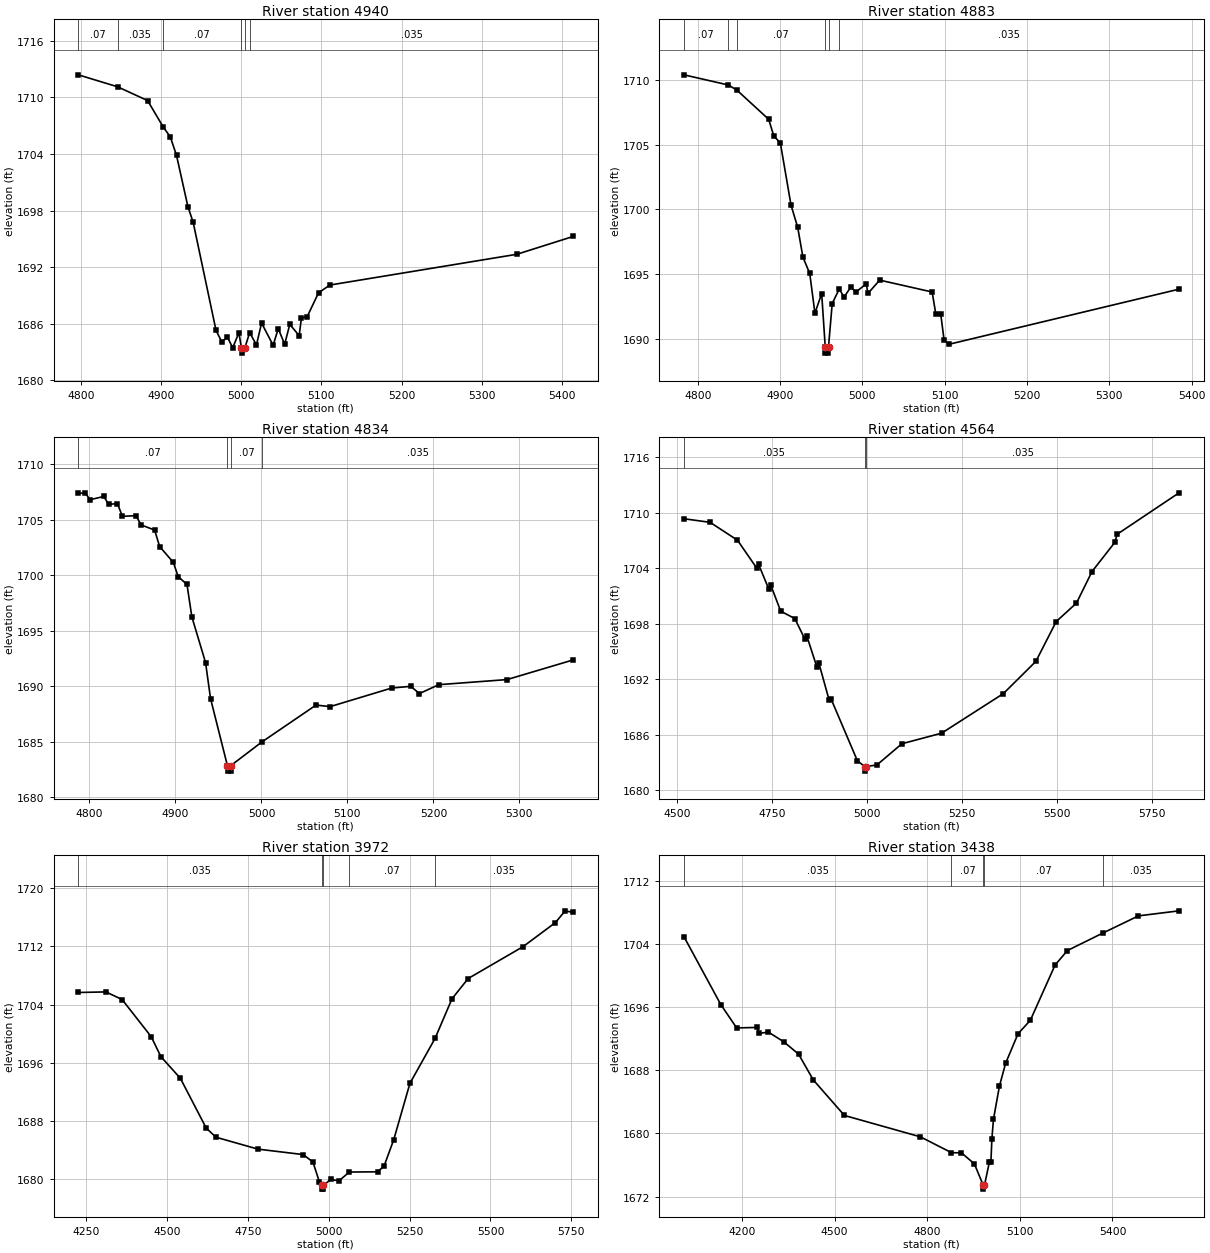
Type RM Length L Ch R = 1,4940,57,57,57
BEGIN DESCRIPTION:
Mapping XS 7a7675a6
END DESCRIPTION:
XS GIS Cut Line= 4
      1682167.93      6993482.52      1682304.65      6993640.95
      1682356.73      6993682.18      1682604.15      6993918.74
#Sta/Elev= 30
  4796.5 1712.40  4845.6 1711.13  4883.0 1709.67  4902.3 1706.90  4911.4 1705.81
  4919.1 1703.86  4933.3 1698.43  4939.9 1696.76  4968.4 1685.31  4975.5 1684.10
  4982.7 1684.56  4989.3 1683.46  4997.0 1685.06  5000.2 1683.39  5000.5 1682.89
  5004.2 1683.39  5010.4 1685.06  5018.9 1683.76  5025.3 1686.08  5039.7 1683.72
  5046.1 1685.49  5054.1 1683.83  5060.5 1685.94  5072.2 1684.74  5075.0 1686.61
  5082.3 1686.77  5096.4 1689.29  5110.6 1690.11  5343.9 1693.37  5414.5 1695.27
#Mann=6,-1,0
  4796.5    0.07       0  4845.6   0.035       0  4902.3    0.07       0
  5000.2    0.07       0  5004.2    0.07       0  5010.4   0.035       0
Bank Sta=5000.2,5004.2
Exp/Cntr=0.3,0.1

Type RM Length L Ch R = 1,4883,49,49,49
BEGIN DESCRIPTION:
Mapping XS 0eb22363
END DESCRIPTION:
XS GIS Cut Line= 4
      1682091.98      6993547.64      1682267.76      6993682.18
      1682335.03      6993738.60      1682510.38      6993972.40
#Sta/Elev= 30
  4783.3 1710.41  4837.4 1709.62  4847.7 1709.22  4886.2 1706.97  4892.5 1705.67
  4900.4 1705.14  4913.3 1700.34  4921.5 1698.60  4927.8 1696.30  4936.1 1695.04
  4942.4 1691.96  4950.6 1693.48  4954.9 1689.37  4955.1 1688.87  4958.6 1688.87
  4958.9 1689.37  4963.4 1692.71  4972.0 1693.84  4977.7 1693.20  4985.9 1693.97
  4992.2 1693.60  5004.7 1694.23  5006.8 1693.49  5021.1 1694.52  5084.8 1693.60
  5089.2 1691.91  5095.2 1691.91  5099.3 1689.87  5105.6 1689.56  5384.7 1693.82
#Mann=6,-1,0
  4783.3    0.07       0  4837.4   0.035       0  4847.7    0.07       0
  4954.9   0.035       0  4958.9    0.07       0  4972.0   0.035       0
Bank Sta=4954.9,4958.9
Exp/Cntr=0.3,0.1

Type RM Length L Ch R = 1,4834,270,270,270
BEGIN DESCRIPTION:
Mapping XS 12e50e39
END DESCRIPTION:
XS GIS Cut Line= 5
      1682044.22      6993608.39      1682209.16      6993701.71
      1682230.87      6993714.73      1682267.76      6993755.96
      1682410.47      6994026.25
#Sta/Elev= 30
  4787.0 1707.38  4795.0 1707.44  4800.7 1706.82  4816.6 1707.11  4822.4 1706.40
  4832.5 1706.47  4838.3 1705.32  4854.2 1705.38  4859.9 1704.55  4875.8 1704.08
  4881.6 1702.59  4897.5 1701.17  4903.2 1699.88  4913.4 1699.17  4919.1 1696.24
  4935.0 1692.13  4940.8 1688.88  4960.4 1682.83  4960.7 1682.33  4964.2 1682.33
  4964.4 1682.83  5000.5 1684.96  5063.5 1688.29  5079.9 1688.15  5151.6 1689.83
  5173.6 1689.98  5183.8 1689.33  5206.3 1690.13  5285.6 1690.59  5362.8 1692.37
#Mann=4,-1,0
  4787.0    0.07       0  4960.4    0.07       0  4964.4    0.07       0
  5000.5   0.035       0
Bank Sta=4960.4,4964.4
Exp/Cntr=0.3,0.1

Type RM Length L Ch R = 1,4564,592,592,592
BEGIN DESCRIPTION:
Mapping XS f48eb36d
END DESCRIPTION:
XS GIS Cut Line= 3
      1681869.68      6993414.06      1682020.71      6993874.98
      1682309.77      6994640.60
#Sta/Elev= 30
  4517.5 1709.33  4586.4 1708.94  4658.4 1707.01  4708.5 1704.03  4713.8 1704.42
  4740.4 1701.78  4745.6 1702.21  4772.2 1699.34  4809.3 1698.55  4835.9 1696.32
  4841.1 1696.64  4867.7 1693.28  4873.0 1693.69  4899.6 1689.75  4904.8 1689.86
  4974.1 1683.18  4993.1 1682.56  4993.3 1682.06  4997.1 1682.56  5025.3 1682.72
  5091.3 1685.02  5195.8 1686.16  5358.5 1690.44  5444.0 1693.92  5497.5 1698.22
  5550.9 1700.22  5591.7 1703.62  5652.1 1706.79  5657.8 1707.65  5820.9 1712.13
#Mann=3,-1,0
  4517.5   0.035       0  4993.1   0.035       0  4997.1   0.035       0
Bank Sta=4993.1,4997.1
Exp/Cntr=0.3,0.1

Type RM Length L Ch R = 1,3972,534,534,534
BEGIN DESCRIPTION:
Mapping XS 39566357
END DESCRIPTION:
XS GIS Cut Line= 3
      1681687.38      6993312.49      1681689.98      6994093.73
      1681689.98      6994843.39
#Sta/Elev= 30
  4225.4 1705.66  4310.9 1705.74  4360.9 1704.69  4450.9 1699.58  4480.9 1696.83
  4540.9 1693.87  4620.9 1687.02  4650.9 1685.76  4780.9 1684.12  4920.9 1683.37
  4950.9 1682.35  4970.9 1679.62  4978.9 1679.12  4979.1 1678.62  4982.7 1678.62
  4983.0 1679.12  5006.3 1679.97  5030.9 1679.75  5063.7 1680.97  5150.9 1681.00
  5170.9 1681.79  5200.9 1685.43  5250.9 1693.17  5328.5 1699.34  5380.9 1704.79
  5430.9 1707.58  5600.9 1711.97  5700.9 1715.28  5730.9 1716.89  5756.3 1716.66
#Mann=5,-1,0
  4225.4   0.035       0  4978.9   0.035       0  4983.0   0.035       0
  5063.7    0.07       0  5328.5   0.035       0
Bank Sta=4978.9,4983
Exp/Cntr=0.3,0.1

Type RM Length L Ch R = 1,3438,617,617,617
BEGIN DESCRIPTION:
Mapping XS f6ea59a5
END DESCRIPTION:
XS GIS Cut Line= 3
      1681523.71      6993121.66      1681300.19      6994087.36
      1681282.82      6994699.38
#Sta/Elev= 30
  4012.2 1704.98  4131.6 1696.36  4182.9 1693.40  4250.0 1693.46  4255.2 1692.70
  4285.6 1692.87  4335.4 1691.64  4383.3 1690.08  4431.1 1686.80  4531.9 1682.29
  4777.8 1679.58  4878.5 1677.57  4911.1 1677.54  4952.8 1676.15  4981.5 1673.44
  4981.8 1672.94  4985.6 1673.44  5001.2 1676.33  5006.3 1676.33  5009.6 1679.35
  5014.6 1681.79  5034.1 1686.04  5054.1 1688.92  5094.1 1692.65  5134.1 1694.37
  5214.2 1701.38  5254.2 1703.22  5368.9 1705.44  5484.3 1707.62  5615.7 1708.26
#Mann=5,-1,0
  4012.2   0.035       0  4878.5    0.07       0  4981.5    0.07       0
  4985.6    0.07       0  5368.9   0.035       0
Bank Sta=4981.5,4985.6
Exp/Cntr=0.3,0.1

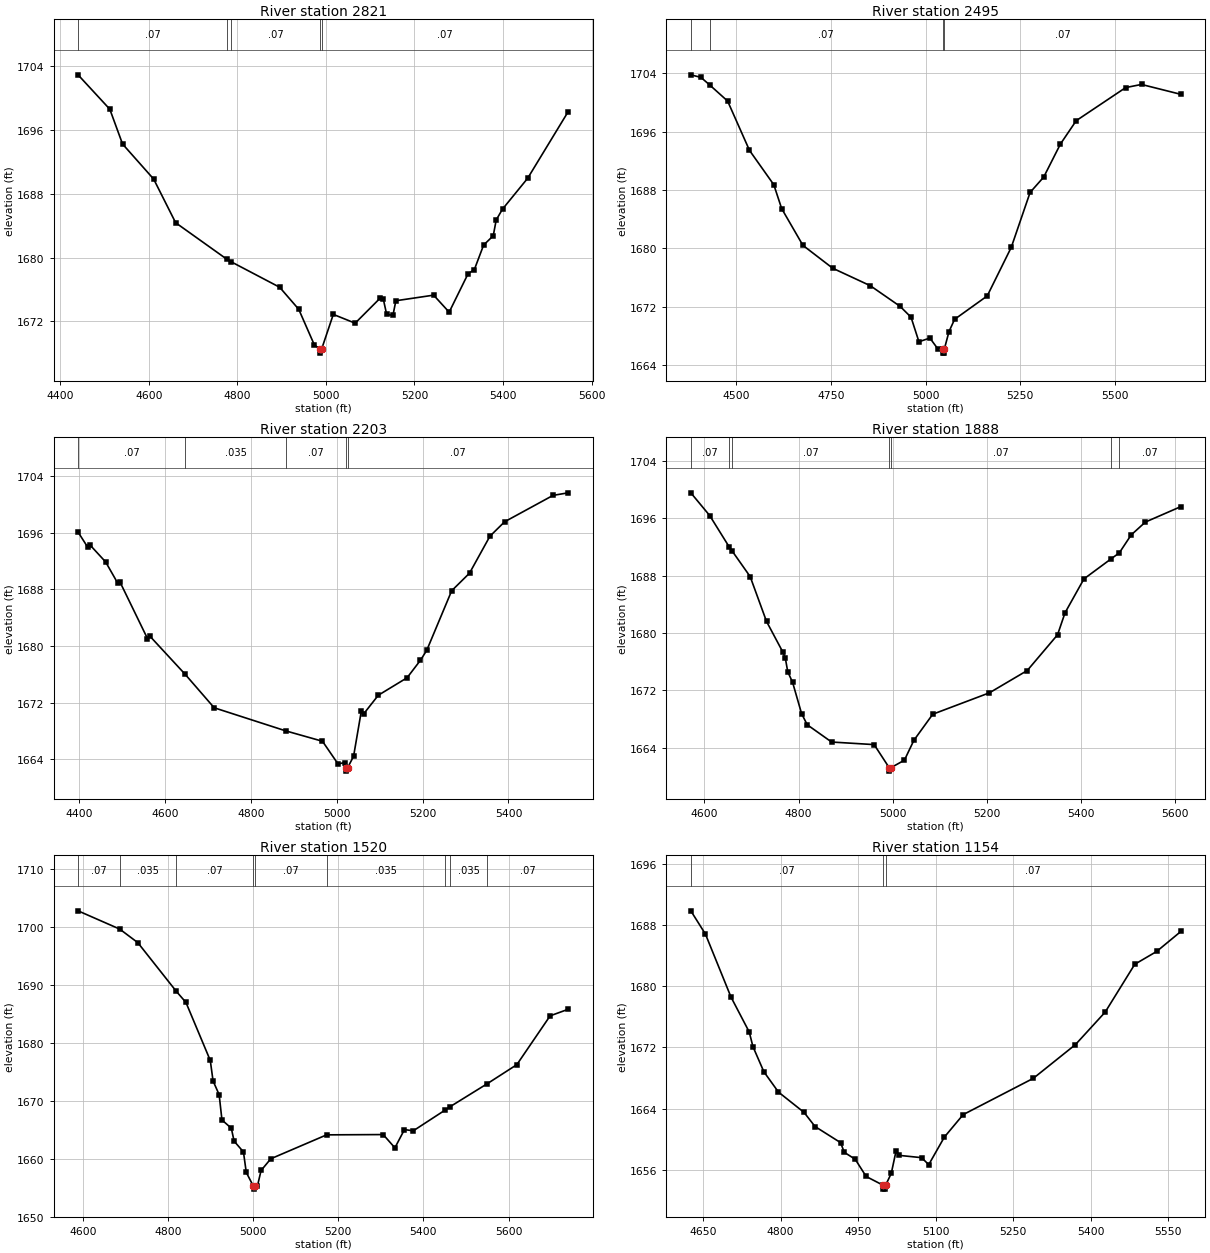
Type RM Length L Ch R = 1,2821,326,326,326
BEGIN DESCRIPTION:
Mapping XS 2372a765
END DESCRIPTION:
XS GIS Cut Line= 3
      1681314.71      6993156.67      1680960.57      6993594.13
      1680599.72      6994001.83
#Sta/Elev= 30
  4439.9 1702.88  4511.7 1698.57  4540.4 1694.22  4610.8 1689.82  4660.4 1684.36
  4776.8 1679.76  4785.4 1679.48  4895.4 1676.28  4938.5 1673.52  4973.7 1669.07
  4986.0 1668.53  4986.3 1668.03  4990.2 1668.53  5016.6 1672.88  5066.0 1671.78
  5122.9 1674.94  5129.5 1674.82  5137.1 1672.90  5151.3 1672.75  5158.0 1674.59
  5243.3 1675.29  5278.4 1673.16  5321.1 1677.97  5335.3 1678.49  5356.2 1681.56
  5378.0 1682.73  5384.7 1684.71  5398.9 1686.06  5455.8 1689.93  5547.2 1698.26
#Mann=5,-1,0
  4439.9    0.07       0  4776.8   0.035       0  4785.4    0.07       0
  4986.0    0.07       0  4990.2    0.07       0
Bank Sta=4986,4990.2
Exp/Cntr=0.3,0.1

Type RM Length L Ch R = 1,2495,292,292,292
BEGIN DESCRIPTION:
Mapping XS 73d27a02
END DESCRIPTION:
XS GIS Cut Line= 3
      1681089.03      6992955.26      1680703.63      6993446.56
      1680317.22      6993994.12
#Sta/Elev= 30
  4379.8 1703.81  4406.5 1703.46  4429.4 1702.43  4477.0 1700.21  4534.8 1693.44
  4599.0 1688.73  4619.8 1685.45  4675.9 1680.41  4754.6 1677.27  4854.0 1674.87
  4932.6 1672.04  4961.5 1670.55  4982.4 1667.18  5011.3 1667.69  5032.2 1666.21
  5044.8 1666.12  5045.1 1665.62  5048.9 1665.62  5049.2 1666.12  5061.8 1668.58
  5076.6 1670.26  5162.8 1673.47  5226.3 1680.14  5276.0 1687.67  5312.0 1689.78
  5356.1 1694.31  5397.9 1697.52  5528.5 1702.06  5570.3 1702.49  5674.4 1701.13
#Mann=4,-1,0
  4379.8   0.035       0  4429.4    0.07       0  5044.8    0.07       0
  5049.2    0.07       0
Bank Sta=5044.8,5049.2
Exp/Cntr=0.3,0.1

Type RM Length L Ch R = 1,2203,315,315,315
BEGIN DESCRIPTION:
Mapping XS e9b36360
END DESCRIPTION:
XS GIS Cut Line= 3
      1680533.84      6992744.46      1680445.30      6993343.44
      1680301.19      6993859.10
#Sta/Elev= 30
  4398.0 1696.08  4420.5 1693.94  4425.6 1694.27  4462.2 1691.86  4490.1 1688.89
  4495.1 1689.09  4559.6 1681.04  4564.7 1681.41  4647.3 1675.99  4714.9 1671.26
  4881.8 1667.99  4967.0 1666.53  5003.3 1663.32  5018.3 1663.52  5021.3 1662.81
  5021.6 1662.31  5025.7 1662.81  5039.4 1664.40  5057.6 1670.85  5062.8 1670.39
  5097.0 1673.03  5164.0 1675.50  5195.1 1677.97  5209.8 1679.38  5267.8 1687.79
  5309.3 1690.27  5356.8 1695.49  5391.0 1697.53  5503.8 1701.26  5538.9 1701.62
#Mann=5,-1,0
  4398.0    0.07       0  4647.3   0.035       0  4881.8    0.07       0
  5021.3    0.07       0  5025.7    0.07       0
Bank Sta=5021.3,5025.7
Exp/Cntr=0.3,0.1

Type RM Length L Ch R = 1,1888,368,368,368
BEGIN DESCRIPTION:
Mapping XS a55de135
END DESCRIPTION:
XS GIS Cut Line= 3
      1680332.44      6992739.29      1680219.60      6993155.94
      1680167.55      6993763.25
#Sta/Elev= 30
  4571.1 1699.58  4611.2 1696.41  4652.4 1692.06  4658.3 1691.52  4697.2 1687.89
  4731.9 1681.64  4766.6 1677.36  4771.8 1676.55  4777.0 1674.62  4787.3 1673.14
  4806.4 1668.78  4818.4 1667.22  4870.2 1664.81  4960.6 1664.45  4992.3 1661.25
  4992.6 1660.75  4996.8 1661.25  5024.9 1662.28  5045.0 1665.05  5085.1 1668.69
  5205.6 1671.68  5285.9 1674.79  5350.2 1679.77  5366.1 1682.84  5406.3 1687.57
  5464.2 1690.38  5481.4 1691.20  5506.7 1693.71  5536.8 1695.50  5612.3 1697.66
#Mann=7,-1,0
  4571.1    0.07       0  4652.4   0.035       0  4658.3    0.07       0
  4992.3    0.07       0  4996.8    0.07       0  5464.2   0.035       0
  5481.4    0.07       0
Bank Sta=4992.3,4996.8
Exp/Cntr=0.3,0.1

Type RM Length L Ch R = 1,1520,366,366,366
BEGIN DESCRIPTION:
Mapping XS 0e407972
END DESCRIPTION:
XS GIS Cut Line= 3
      1680271.94      6992627.86      1679952.92      6992899.14
      1679509.03      6993481.61
#Sta/Elev= 30
  4588.8 1702.85  4686.6 1699.70  4729.1 1697.36  4819.8 1688.93  4842.2 1687.04
  4899.4 1677.01  4905.9 1673.48  4920.2 1671.11  4926.8 1666.74  4948.8 1665.32
  4955.3 1663.09  4977.3 1661.22  4983.9 1657.69  5000.7 1655.30  5001.0 1654.80
  5005.2 1655.30  5010.0 1655.30  5018.7 1658.02  5041.5 1660.04  5172.6 1664.17
  5305.5 1664.22  5333.0 1661.93  5355.4 1665.08  5376.2 1664.87  5451.2 1668.46
  5462.6 1669.03  5550.1 1673.01  5619.4 1676.29  5697.6 1684.72  5739.9 1685.85
#Mann=9,-1,0
  4588.8    0.07       0  4686.6   0.035       0  4819.8    0.07       0
  5000.7    0.07       0  5005.2    0.07       0  5172.6   0.035       0
  5451.2    0.07       0  5462.6   0.035       0  5550.1    0.07       0
Bank Sta=5000.7,5005.2
Exp/Cntr=0.3,0.1

Type RM Length L Ch R = 1,1154,289,289,289
BEGIN DESCRIPTION:
Mapping XS 66fb47a1
END DESCRIPTION:
XS GIS Cut Line= 3
      1679861.80      6992614.83      1679590.51      6992883.94
      1679282.32      6993359.25
#Sta/Elev= 30
  4626.3 1689.85  4654.6 1686.81  4704.1 1678.58  4739.4 1674.02  4746.5 1672.12
  4767.7 1668.83  4796.0 1666.17  4845.5 1663.52  4866.7 1661.68  4916.2 1659.57
  4923.3 1658.31  4944.5 1657.40  4965.7 1655.15  4998.8 1654.00  4999.1 1653.50
  5003.0 1653.50  5003.3 1654.00  5014.3 1655.56  5023.5 1658.47  5029.4 1657.91
  5072.9 1657.61  5086.8 1656.70  5117.1 1660.30  5153.4 1663.23  5289.2 1667.97
  5370.8 1672.38  5428.3 1676.62  5485.6 1682.87  5527.9 1684.54  5574.9 1687.16
#Mann=3,-1,0
  4626.3    0.07       0  4998.8    0.07       0  5003.3    0.07       0
Bank Sta=4998.8,5003.3
Exp/Cntr=0.3,0.1

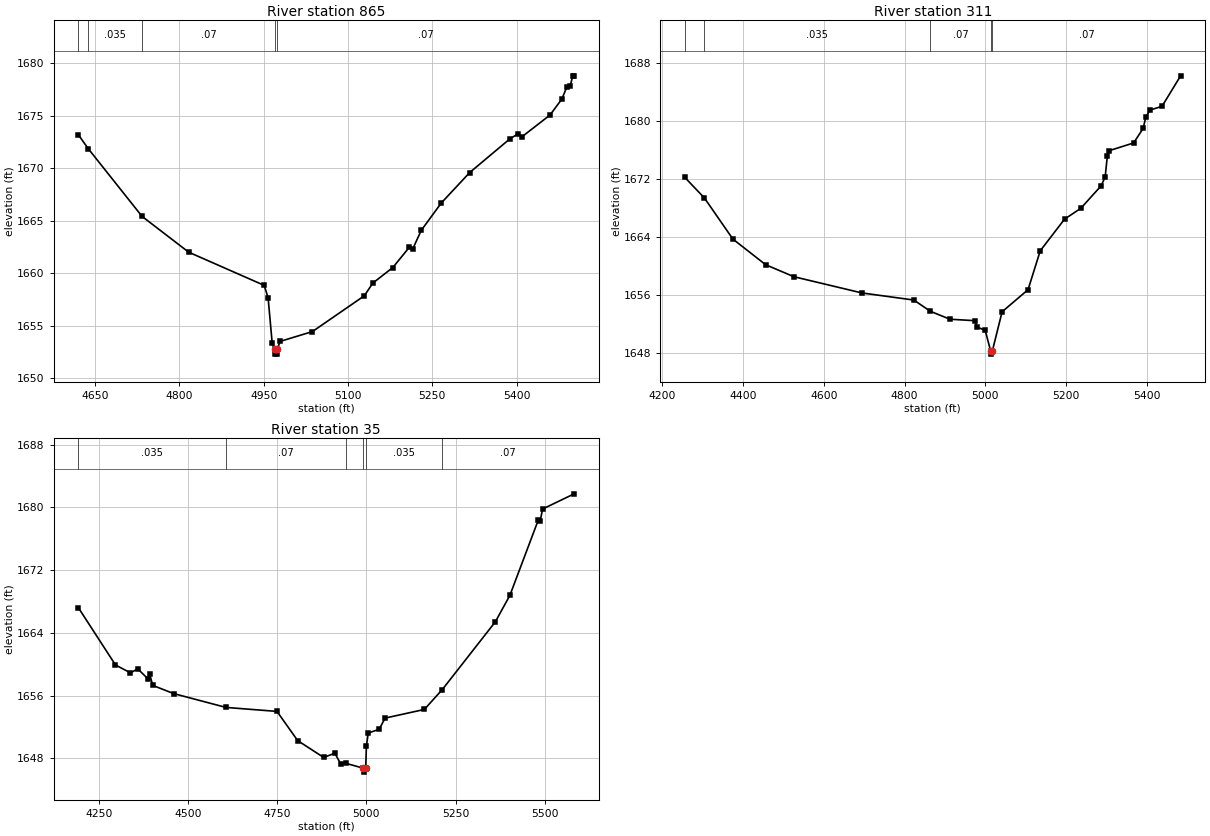
Type RM Length L Ch R = 1,865,554,554,554
BEGIN DESCRIPTION:
Mapping XS 91a81165
END DESCRIPTION:
XS GIS Cut Line= 3
      1679647.16      6992492.57      1679371.12      6992758.19
      1679084.67      6993167.04
#Sta/Elev= 30
  4620.2 1673.19  4638.0 1671.85  4733.6 1665.41  4816.6 1662.00  4950.9 1658.84
  4957.9 1657.66  4965.1 1653.37  4969.6 1652.79  4970.0 1652.29  4974.1 1652.29
  4974.4 1652.79  4979.2 1653.50  5036.8 1654.44  5129.2 1657.85  5144.1 1659.05
  5179.8 1660.54  5209.4 1662.48  5215.6 1662.35  5230.4 1664.08  5266.1 1666.69
  5316.7 1669.59  5388.2 1672.80  5403.0 1673.28  5409.1 1672.97  5459.6 1675.07
  5480.6 1676.59  5489.3 1677.71  5495.4 1677.82  5500.0 1678.80  5502.5 1678.80
#Mann=5,-1,0
  4620.2    0.07       0  4638.0   0.035       0  4733.6    0.07       0
  4969.6    0.07       0  4974.4    0.07       0
Bank Sta=4969.6,4974.4
Exp/Cntr=0.3,0.1

Type RM Length L Ch R = 1,311,276,276,276
BEGIN DESCRIPTION:
Mapping XS ec29bf2d
END DESCRIPTION:
XS GIS Cut Line= 3
      1679587.29      6992444.38      1678904.98      6992742.57
      1678849.06      6993223.70
#Sta/Elev= 30
  4255.3 1672.26  4303.9 1669.42  4374.5 1663.74  4455.7 1660.20  4525.9 1658.54
  4694.3 1656.30  4823.0 1655.32  4864.2 1653.76  4912.6 1652.67  4974.3 1652.47
  4979.8 1651.59  4999.9 1651.14  5013.1 1648.35  5013.4 1647.85  5017.9 1648.35
  5041.8 1653.70  5106.1 1656.75  5136.3 1662.12  5196.7 1666.50  5236.9 1667.99
  5287.3 1671.10  5297.3 1672.33  5302.6 1675.19  5307.7 1675.96  5367.8 1677.02
  5391.3 1679.02  5398.0 1680.57  5408.1 1681.55  5438.3 1682.09  5484.3 1686.29
#Mann=5,-1,0
  4255.3    0.07       0  4303.9   0.035       0  4864.2    0.07       0
  5013.1    0.07       0  5017.9    0.07       0
Bank Sta=5013.1,5017.9
Exp/Cntr=0.3,0.1

Type RM Length L Ch R = 1,35,0,0,0
BEGIN DESCRIPTION:
Chimney Creek 1168 1.0
END DESCRIPTION:
XS GIS Cut Line= 3
      1679454.99      6992388.00      1678680.00      6992613.03
      1678571.97      6993184.82
#Sta/Elev= 30
  4193.0 1667.23  4297.1 1659.92  4338.8 1658.92  4359.6 1659.42  4387.9 1658.16
  4393.1 1658.72  4401.3 1657.32  4460.2 1656.27  4606.5 1654.51  4749.5 1654.00
  4807.4 1650.28  4880.3 1648.13  4911.5 1648.67  4927.6 1647.34  4942.0 1647.39
  4991.4 1646.76  4991.9 1646.26  4998.0 1646.76  4999.9 1649.57  5005.1 1651.24
  5035.6 1651.72  5052.4 1653.15  5162.2 1654.25  5212.6 1656.79  5361.2 1665.43
  5402.0 1668.81  5481.5 1678.41  5486.6 1678.26  5493.5 1679.80  5581.9 1681.74
#Mann=6,-1,0
  4193.0   0.035       0  4606.5    0.07       0  4942.0   0.035       0
  4991.4   0.035       0  4998.0   0.035       0  5212.6    0.07       0
Bank Sta=4991.4,4998
Exp/Cntr=0.3,0.1

Chan Stop Cuts=-1