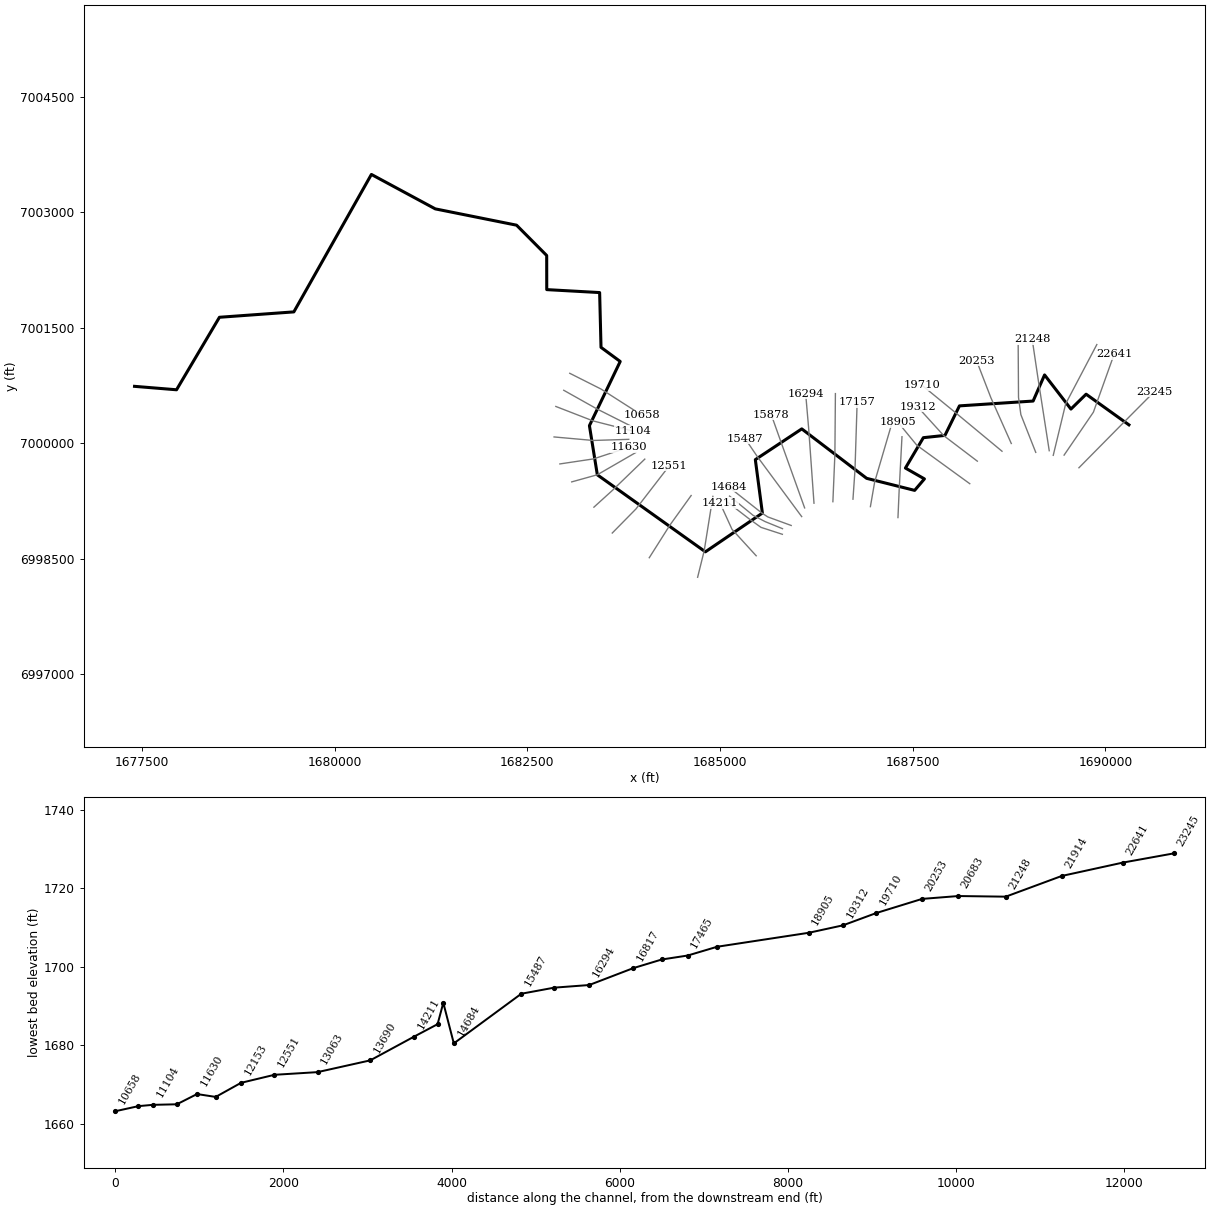
--- Chimney Creek 1169.prj (project) ---

Proj Title=Chimney Creek 1169 Base Level Engineering
Current Plan=p01
Default Exp/Contr=0.3,0.1
English Units
Geom File=g01
Flow File=f01
Plan File=p01
BEGIN DESCRIPTION:
Chimney Creek 1169
END DESCRIPTION:

--- Chimney Creek 1169.p01 (plan) ---

Plan Title=Multiple Run
Short Identifier=Multiple
Geom File=g01
Flow File=f01
Subcritical Flow
K Sum by GR= 0
Std Step Tol= 0.01
Critical Tol= 0.01
Num of Std Step Trials= 20
Max Error Tol= 0.3
Flow Tol Ratio= 0.001
Split Flow NTrial= 30
Split Flow Tol= 0.02
Split Flow Ratio= 0.02
Log Output Level= 0
Friction Slope Method= 1
Unsteady Friction Slope Method= 2
Unsteady Bridges Friction Slope Method= 1
Parabolic Critical Depth
Global Vel Dist=  1 , 1 , 1
Global Log Level= 0
CheckData=True
Encroach Param= -1, 0, 0, 0
BEGIN DESCRIPTION:
Multiple Run
END DESCRIPTION:

--- Chimney Creek 1169.f01 (steady flow) ---

Flow Title=Multiple
Number of Profiles=7
Profile Names=10-year,25-year,50-year,1pct_min,100-year,1pct_plu,500-year
River Rch & RM= Chimney Creek 11,Reach-1,23245
     226     308     375     228     455     907     674
River Rch & RM= Chimney Creek 11,Reach-1,22641
     336     467     575     352     703    1402    1064
River Rch & RM= Chimney Creek 11,Reach-1,13690
     443     624     776     480     957    1909    1474
River Rch & RM= Chimney Creek 11,Reach-1,7252
     578     825    1035     645    1288    2570    2018
River Rch & RM= Chimney Creek 11,Reach-1,559
     683     984    1242     778    1553    3099    2460
Boundary for River Rch & Prof#=Chimney Creek 11,Reach-1,1
Up Type=0
Dn Type=3
Dn Slope=0.005
Boundary for River Rch & Prof#=Chimney Creek 11,Reach-1,2
Up Type=0
Dn Type=3
Dn Slope=0.005
Boundary for River Rch & Prof#=Chimney Creek 11,Reach-1,3
Up Type=0
Dn Type=3
Dn Slope=0.005
Boundary for River Rch & Prof#=Chimney Creek 11,Reach-1,4
Up Type=0
Dn Type=3
Dn Slope=0.005
Boundary for River Rch & Prof#=Chimney Creek 11,Reach-1,5
Up Type=0
Dn Type=3
Dn Slope=0.005
Boundary for River Rch & Prof#=Chimney Creek 11,Reach-1,6
Up Type=0
Dn Type=3
Dn Slope=0.005
Boundary for River Rch & Prof#=Chimney Creek 11,Reach-1,7
Up Type=0
Dn Type=3
Dn Slope=0.005

--- Chimney Creek 1169.g01 (geometry) ---

Geom Title=Existing Conditions

River Reach=Chimney Creek 11,Reach-1
Reach XY= 30
      1690305.00      7000238.00      1689749.63      7000636.05
      1689552.74      7000443.05      1689210.75      7000886.14
      1689062.12      7000547.01      1688106.48      7000484.39
      1687918.38      7000101.37      1687638.20      7000071.59
      1687405.68      6999677.25      1687652.01      6999536.60
      1687525.18      6999387.57      1686902.71      6999543.85
      1686060.95      7000185.75      1685458.53      6999786.53
      1685549.97      6999093.08      1684810.71      6998589.88
      1683408.76      6999589.56      1683306.20      7000227.49
      1683705.65      7001060.78      1683456.57      7001244.04
      1683438.73      7001955.22      1682752.55      7001993.47
      1682751.90      7002436.35      1682361.06      7002829.86
      1681306.47      7003041.55      1680477.78      7003488.60
      1679471.76      7001704.43      1678506.46      7001634.48
      1677949.76      7000693.44      1677405.00      7000738.00

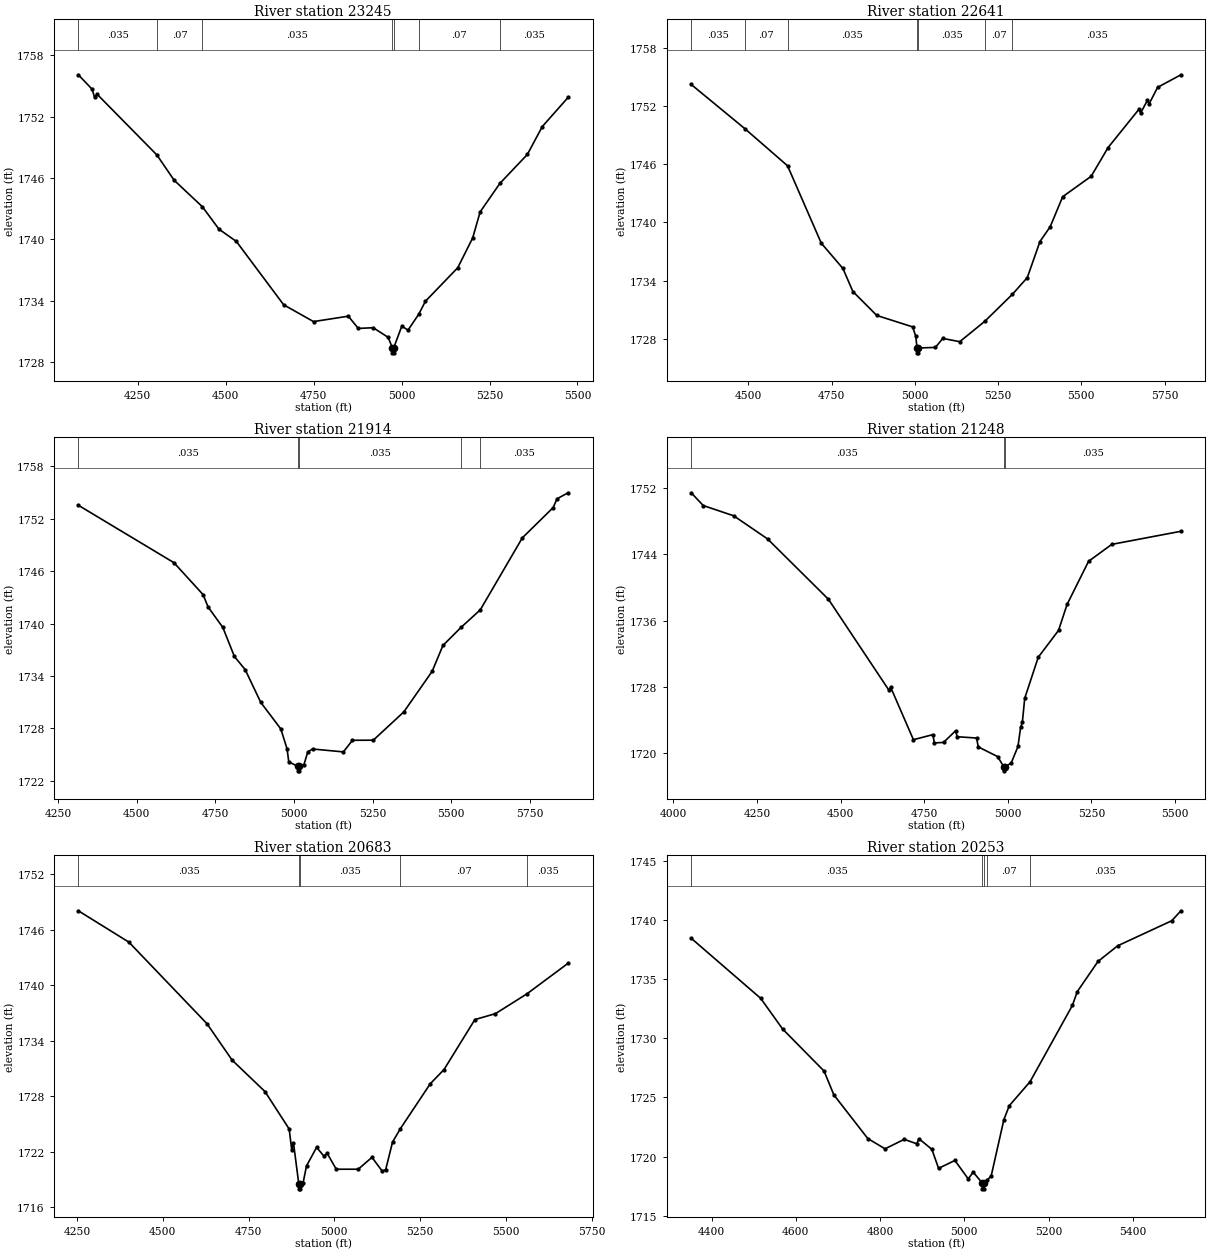
Type RM Length L Ch R = 1,23245,604,604,604
BEGIN DESCRIPTION:
Chimney Creek 1169 47.0
END DESCRIPTION:
XS GIS Cut Line= 3
      1689656.64      6999681.09      1690305.00      7000338.00
      1690635.85      7000670.72
#Sta/Elev= 30
  4081.1 1756.11  4120.1 1754.70  4127.3 1753.91  4134.3 1754.21  4304.3 1748.26
  4353.5 1745.78  4433.9 1743.18  4480.8 1740.99  4530.3 1739.79  4664.7 1733.59
  4749.6 1731.94  4848.6 1732.47  4876.8 1731.27  4919.3 1731.34  4961.7 1730.40
  4973.8 1729.38  4974.1 1728.88  4977.6 1728.88  4977.8 1729.38  5000.6 1731.50
  5018.2 1731.10  5048.8 1732.66  5067.7 1733.93  5159.6 1737.21  5202.1 1740.13
  5223.3 1742.68  5279.6 1745.48  5357.6 1748.31  5400.0 1751.04  5473.3 1753.89
#Mann=7,-1,0
  4081.1   0.035       0  4304.3    0.07       0  4433.9   0.035       0
  4973.8   0.035       0  4977.8   0.035       0  5048.8    0.07       0
  5279.6   0.035       0
Bank Sta=4973.8,4977.8
Exp/Cntr=0.3,0.1

Type RM Length L Ch R = 1,22641,727,727,727
BEGIN DESCRIPTION:
Mapping XS e56a4883
END DESCRIPTION:
XS GIS Cut Line= 3
      1689463.96      6999845.19      1689844.15      7000402.46
      1690112.37      7001152.43
#Sta/Elev= 30
  4328.2 1754.25  4488.9 1749.70  4617.7 1745.85  4719.0 1737.86  4784.0 1735.25
  4813.9 1732.87  4885.7 1730.40  4993.4 1729.22  5002.8 1728.24  5006.6 1727.04
  5006.9 1726.54  5010.5 1726.54  5010.7 1727.04  5061.8 1727.10  5084.0 1728.03
  5134.9 1727.69  5210.3 1729.80  5293.2 1732.59  5337.9 1734.31  5375.8 1738.03
  5406.6 1739.56  5444.1 1742.66  5529.7 1744.77  5580.6 1747.74  5673.0 1751.68
  5678.3 1751.30  5698.4 1752.60  5703.8 1752.25  5729.2 1753.95  5799.3 1755.25
#Mann=7,-1,0
  4328.2   0.035       0  4488.9    0.07       0  4617.7   0.035       0
  5006.6   0.035       0  5010.7   0.035       0  5210.3    0.07       0
  5293.2   0.035       0
Bank Sta=5006.6,5010.7
Exp/Cntr=0.3,0.1

Type RM Length L Ch R = 1,21914,666,666,666
BEGIN DESCRIPTION:
Mapping XS d6ddbe15
END DESCRIPTION:
XS GIS Cut Line= 3
      1689323.32      6999842.56      1689484.78      7000511.83
      1689888.43      7001280.07
#Sta/Elev= 30
  4314.7 1753.55  4618.6 1746.97  4711.2 1743.31  4726.8 1741.91  4773.8 1739.56
  4810.6 1736.23  4844.9 1734.72  4894.4 1730.97  4958.1 1727.93  4978.2 1725.62
  4983.3 1724.16  5013.0 1723.63  5013.3 1723.13  5016.9 1723.13  5017.1 1723.63
  5031.5 1723.83  5044.0 1725.31  5059.2 1725.63  5157.0 1725.30  5185.8 1726.63
  5252.0 1726.64  5349.0 1729.88  5439.1 1734.53  5473.3 1737.49  5531.1 1739.57
  5592.0 1741.57  5725.7 1749.82  5823.5 1753.28  5835.9 1754.29  5871.0 1754.98
#Mann=5,-1,0
  4314.7   0.035       0  5013.0   0.035       0  5017.1   0.035       0
  5531.1    0.07       0  5592.0   0.035       0
Bank Sta=5013,5017.1
Exp/Cntr=0.3,0.1

Type RM Length L Ch R = 1,21248,565,565,565
BEGIN DESCRIPTION:
Mapping XS 4ccc633d
END DESCRIPTION:
XS GIS Cut Line= 3
      1689271.24      6999902.42      1689125.40      7000842.56
      1689049.94      7001350.00
#Sta/Elev= 30
  4053.4 1751.43  4089.4 1749.89  4180.5 1748.65  4281.7 1745.86  4463.8 1738.57
  4644.8 1727.58  4649.8 1727.95  4717.9 1721.61  4775.8 1722.22  4780.8 1721.22
  4807.9 1721.28  4843.8 1722.68  4848.9 1721.97  4906.8 1721.81  4911.8 1720.74
  4969.8 1719.57  4987.9 1718.35  4988.2 1717.85  4992.2 1718.35  5010.3 1718.79
  5030.5 1720.79  5038.5 1723.12  5043.6 1723.69  5050.7 1726.61  5091.2 1731.57
  5151.8 1734.81  5177.3 1737.94  5241.6 1743.15  5311.0 1745.20  5517.8 1746.78
#Mann=3,-1,0
  4053.4   0.035       0  4987.9   0.035       0  4992.2   0.035       0
Bank Sta=4987.9,4992.2
Exp/Cntr=0.3,0.1

Type RM Length L Ch R = 1,20683,430,430,430
BEGIN DESCRIPTION:
Mapping XS c9d10eb5
END DESCRIPTION:
XS GIS Cut Line= 4
      1689096.24      6999880.85      1688903.11      7000371.28
      1688872.72      7000594.80      1688868.38      7001269.72
#Sta/Elev= 30
  4253.9 1748.04  4401.3 1744.65  4629.0 1735.84  4702.2 1731.91  4797.9 1728.52
  4868.5 1724.47  4875.9 1722.21  4881.0 1722.98  4896.6 1718.51  4896.9 1718.01
  4900.6 1718.01  4900.9 1718.51  4908.9 1718.63  4919.0 1720.48  4948.4 1722.49
  4969.4 1721.56  4979.5 1721.83  5005.7 1720.13  5069.8 1720.13  5109.8 1721.41
  5139.8 1719.92  5149.8 1720.08  5169.8 1723.06  5192.7 1724.51  5279.8 1729.36
  5319.8 1730.89  5409.8 1736.29  5469.8 1736.93  5562.0 1739.08  5681.5 1742.37
#Mann=5,-1,0
  4253.9   0.035       0  4896.6   0.035       0  4900.9   0.035       0
  5192.7    0.07       0  5562.0   0.035       0
Bank Sta=4896.6,4900.9
Exp/Cntr=0.3,0.1

Type RM Length L Ch R = 1,20253,543,543,543
BEGIN DESCRIPTION:
Mapping XS 36a4c66b
END DESCRIPTION:
XS GIS Cut Line= 3
      1688778.99      6999996.12      1688515.09      7000588.18
      1688329.66      7001068.20
#Sta/Elev= 30
  4351.5 1738.45  4516.6 1733.37  4568.6 1730.78  4667.0 1727.23  4690.2 1725.22
  4770.8 1721.53  4811.8 1720.66  4857.2 1721.46  4887.0 1721.09  4892.4 1721.51
  4922.9 1720.62  4938.9 1719.01  4977.6 1719.68  5009.3 1718.12  5021.0 1718.69
  5042.5 1717.78  5042.8 1717.28  5046.6 1717.28  5046.9 1717.78  5053.7 1717.99
  5063.8 1718.37  5093.9 1723.12  5106.7 1724.30  5156.1 1726.33  5256.8 1732.79
  5268.2 1733.94  5317.4 1736.49  5364.0 1737.81  5492.6 1739.93  5514.3 1740.77
#Mann=5,-1,0
  4351.5   0.035       0  5042.5   0.035       0  5046.9   0.035       0
  5053.7    0.07       0  5156.1   0.035       0
Bank Sta=5042.5,5046.9
Exp/Cntr=0.3,0.1

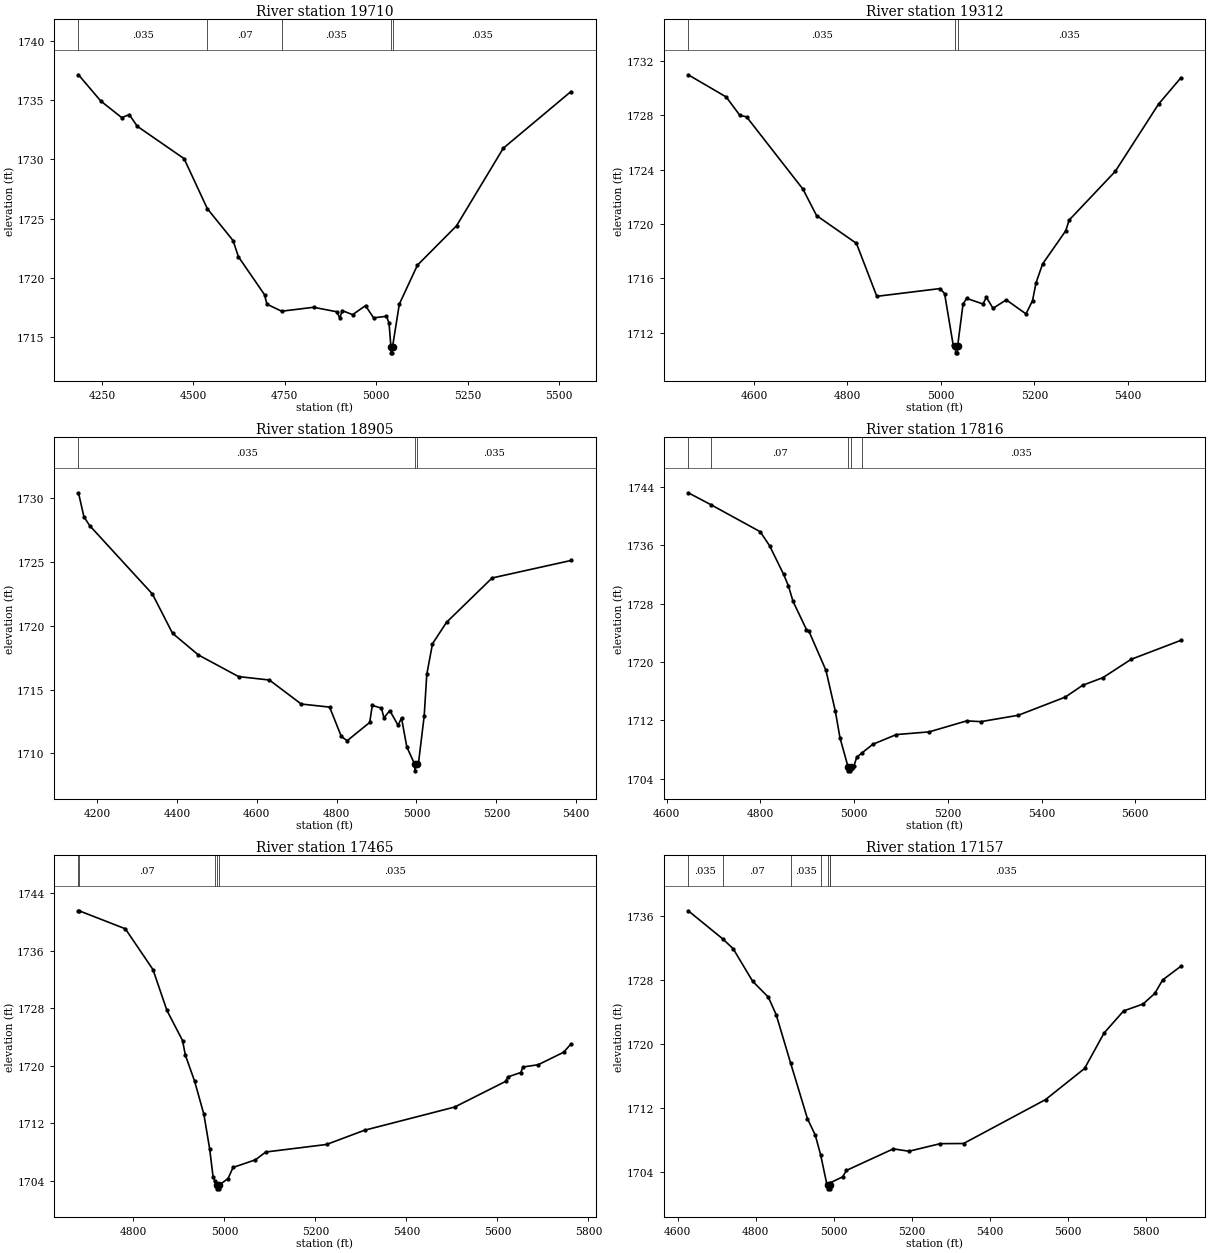
Type RM Length L Ch R = 1,19710,398,398,398
BEGIN DESCRIPTION:
Mapping XS ca1fb93a
END DESCRIPTION:
XS GIS Cut Line= 3
      1688658.66      6999895.65      1688026.72      7000419.95
      1687619.55      7000752.61
#Sta/Elev= 30
  4185.7 1737.13  4246.6 1734.92  4303.9 1733.52  4324.7 1733.77  4346.4 1732.79
  4474.5 1730.06  4538.1 1725.84  4608.6 1723.15  4622.9 1721.80  4694.5 1718.59
  4701.0 1717.79  4741.2 1717.20  4828.6 1717.53  4892.5 1717.15  4900.3 1716.61
  4906.8 1717.25  4935.4 1716.91  4970.6 1717.67  4992.7 1716.64  5027.9 1716.77
  5034.9 1716.21  5040.1 1714.19  5040.4 1713.69  5044.2 1713.69  5044.5 1714.19
  5063.1 1717.80  5112.6 1721.08  5219.6 1724.40  5347.4 1730.94  5532.6 1735.72
#Mann=5,-1,0
  4185.7   0.035       0  4538.1    0.07       0  4741.2   0.035       0
  5040.1   0.035       0  5044.5   0.035       0
Bank Sta=5040.1,5044.5
Exp/Cntr=0.3,0.1

Type RM Length L Ch R = 1,19312,407,407,407
BEGIN DESCRIPTION:
Mapping XS 398cfc53
END DESCRIPTION:
XS GIS Cut Line= 3
      1688338.43      6999766.80      1687904.38      7000096.69
      1687562.57      7000473.19
#Sta/Elev= 30
  4459.5 1730.96  4540.7 1729.33  4569.7 1727.99  4584.3 1727.87  4704.9 1722.56
  4734.0 1720.62  4819.3 1718.58  4862.9 1714.69  4998.1 1715.26  5007.9 1714.89
  5026.4 1711.09  5031.2 1711.04  5031.5 1710.54  5035.4 1710.54  5035.8 1711.04
  5047.3 1714.10  5054.8 1714.54  5089.9 1714.13  5097.4 1714.61  5111.5 1713.81
  5139.9 1714.43  5182.0 1713.40  5196.0 1714.37  5203.5 1715.68  5217.6 1717.07
  5267.0 1719.50  5274.4 1720.29  5373.1 1723.87  5465.7 1728.81  5513.2 1730.73
#Mann=3,-1,0
  4459.5   0.035       0  5031.2   0.035       0  5035.8   0.035       0
Bank Sta=5031.2,5035.8
Exp/Cntr=0.3,0.1

Type RM Length L Ch R = 1,18905,1089,1089,1089
BEGIN DESCRIPTION:
Mapping XS 3cb4416b
END DESCRIPTION:
XS GIS Cut Line= 3
      1688240.14      6999474.34      1687553.95      6999973.03
      1687309.57      7000270.70
#Sta/Elev= 30
  4153.6 1730.41  4167.2 1728.53  4181.9 1727.83  4338.8 1722.48  4389.1 1719.41
  4454.0 1717.71  4554.5 1716.02  4631.7 1715.75  4711.4 1713.87  4782.5 1713.63
  4811.8 1711.33  4826.5 1711.00  4882.9 1712.43  4889.3 1713.76  4912.3 1713.55
  4918.5 1712.79  4933.2 1713.36  4954.0 1712.20  4962.5 1712.79  4975.8 1710.51
  4995.8 1709.14  4996.1 1708.64  5000.4 1709.14  5005.0 1709.24  5019.3 1712.93
  5025.8 1716.19  5040.1 1718.59  5075.3 1720.27  5189.4 1723.74  5387.0 1725.11
#Mann=3,-1,0
  4153.6   0.035       0  4995.8   0.035       0  5000.4   0.035       0
Bank Sta=4995.8,5000.4
Exp/Cntr=0.3,0.1

Type RM Length L Ch R = 1,17816,351,351,351
BEGIN DESCRIPTION:
Mapping XS cd78ff42
END DESCRIPTION:
XS GIS Cut Line= 3
      1687308.89      6999034.58      1687324.52      6999393.99
      1687360.92      7000083.98
#Sta/Elev= 30
  4646.3 1743.19  4694.8 1741.55  4799.9 1737.85  4819.9 1735.92  4849.9 1731.99
  4859.9 1730.44  4869.9 1728.30  4898.5 1724.44  4903.5 1724.25  4940.0 1718.86
  4960.0 1713.28  4970.0 1709.60  4987.4 1705.58  4987.8 1705.08  4992.2 1705.08
  4992.6 1705.58  5000.1 1705.81  5005.6 1706.93  5017.1 1707.55  5040.1 1708.72
  5090.2 1710.05  5160.3 1710.42  5240.4 1711.93  5270.4 1711.82  5350.5 1712.70
  5450.7 1715.19  5487.7 1716.81  5530.8 1717.85  5590.9 1720.36  5697.0 1722.96
#Mann=5,-1,0
  4646.3   0.035       0  4694.8    0.07       0  4987.4    0.07       0
  4992.6    0.07       0  5017.1   0.035       0
Bank Sta=4987.4,4992.6
Exp/Cntr=0.3,0.1

Type RM Length L Ch R = 1,17465,308,308,308
BEGIN DESCRIPTION:
Mapping XS 04970bc0
END DESCRIPTION:
XS GIS Cut Line= 3
      1686951.25      6999176.55      1687006.81      6999497.73
      1687219.85      7000223.46
#Sta/Elev= 30
  4679.3 1741.57  4680.7 1741.57  4782.3 1739.06  4843.0 1733.38  4873.6 1727.70
  4907.9 1723.50  4914.2 1721.46  4934.5 1717.83  4954.8 1713.23  4967.6 1708.39
  4975.1 1704.49  4979.1 1703.88  4982.6 1703.34  4983.0 1702.84  4987.4 1702.84
  4987.8 1703.34  5008.0 1704.27  5018.9 1705.82  5068.1 1706.88  5090.8 1707.97
  5224.4 1709.02  5307.8 1711.00  5505.8 1714.23  5617.7 1717.80  5622.9 1718.43
  5651.1 1719.04  5656.3 1719.81  5689.6 1720.13  5745.5 1721.87  5761.6 1723.03
#Mann=5,-1,0
  4679.3   0.035       0  4680.7    0.07       0  4979.1   0.035       0
  4982.6   0.035       0  4987.8   0.035       0
Bank Sta=4982.6,4987.8
Exp/Cntr=0.3,0.1

Type RM Length L Ch R = 1,17157,340,340,340
BEGIN DESCRIPTION:
Mapping XS f9a64b41
END DESCRIPTION:
XS GIS Cut Line= 3
      1686725.13      6999273.17      1686751.17      6999648.60
      1686779.33      7000534.62
#Sta/Elev= 30
  4627.0 1736.67  4715.1 1733.16  4742.1 1731.92  4792.2 1727.83  4832.3 1725.85
  4852.4 1723.66  4889.2 1717.63  4932.6 1710.62  4952.6 1708.57  4966.5 1706.07
  4982.1 1702.46  4984.5 1702.33  4984.9 1701.83  4989.3 1701.83  4989.7 1702.33
  4991.7 1702.60  5022.7 1703.33  5032.7 1704.14  5152.8 1706.84  5192.8 1706.54
  5272.9 1707.49  5332.9 1707.51  5543.0 1713.01  5643.1 1716.91  5693.1 1721.35
  5743.1 1724.12  5793.1 1724.99  5823.1 1726.31  5843.2 1728.00  5889.8 1729.71
#Mann=7,-1,0
  4627.0   0.035       0  4715.1    0.07       0  4889.2   0.035       0
  4966.5    0.07       0  4984.5   0.035       0  4989.7    0.07       0
  4991.7   0.035       0
Bank Sta=4984.5,4989.7
Exp/Cntr=0.3,0.1

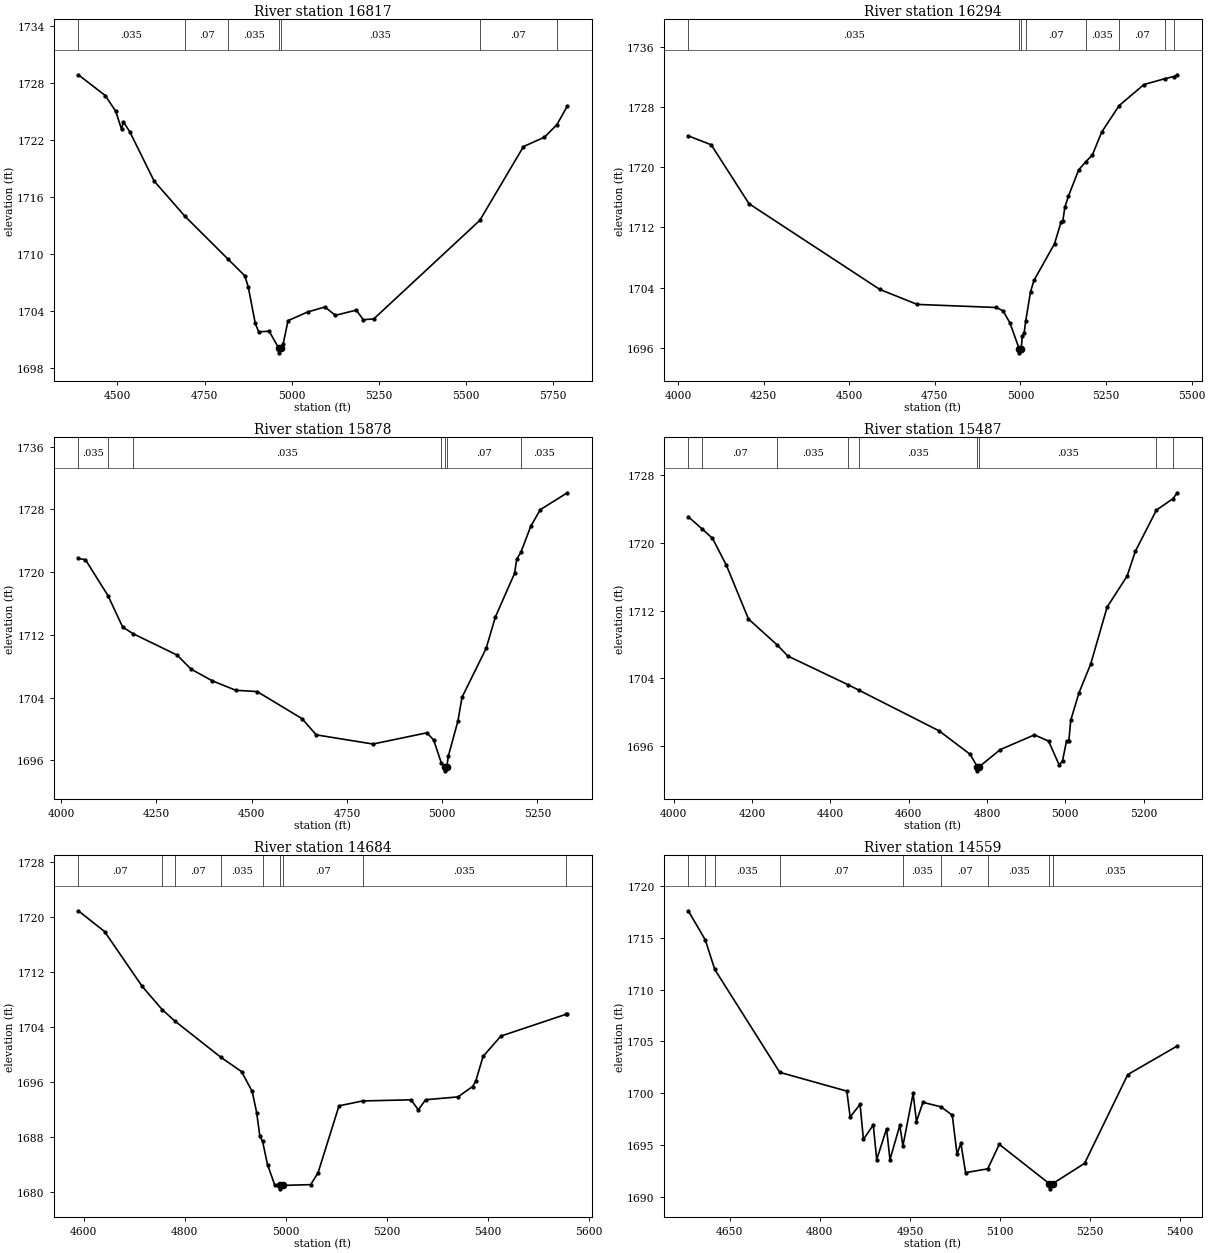
Type RM Length L Ch R = 1,16817,523,523,523
BEGIN DESCRIPTION:
Mapping XS 39e244bb
END DESCRIPTION:
XS GIS Cut Line= 3
      1686464.71      6999240.57      1686490.75      6999859.10
      1686497.25      7000643.80
#Sta/Elev= 30
  4387.5 1728.91  4465.0 1726.72  4495.0 1725.06  4511.7 1723.16  4516.7 1723.97
  4535.1 1722.92  4605.1 1717.72  4692.8 1714.04  4818.1 1709.46  4865.4 1707.74
  4875.4 1706.56  4895.4 1702.74  4905.4 1701.83  4935.4 1701.90  4962.8 1700.12
  4963.2 1699.62  4968.1 1700.12  4975.4 1700.53  4989.6 1703.01  5045.5 1703.92
  5095.5 1704.45  5125.5 1703.57  5185.5 1704.12  5205.5 1703.11  5235.5 1703.19
  5540.0 1713.57  5665.5 1721.35  5725.5 1722.33  5761.6 1723.66  5791.3 1725.62
#Mann=7,-1,0
  4387.5   0.035       0  4692.8    0.07       0  4818.1   0.035       0
  4962.8   0.035       0  4968.1   0.035       0  5540.0    0.07       0
  5761.6   0.035       0
Bank Sta=4962.8,4968.1
Exp/Cntr=0.3,0.1

Type RM Length L Ch R = 1,16294,416,416,416
BEGIN DESCRIPTION:
Mapping XS 3bc42454
END DESCRIPTION:
XS GIS Cut Line= 3
      1686219.48      6999221.10      1686150.04      7000195.47
      1686111.14      7000644.95
#Sta/Elev= 30
  4030.0 1724.17  4097.1 1722.98  4207.4 1715.15  4589.4 1703.75  4698.6 1701.76
  4929.2 1701.35  4949.2 1700.91  4969.3 1699.31  4996.7 1695.82  4997.1 1695.32
  5002.1 1695.82  5005.6 1697.56  5010.8 1697.92  5015.5 1699.59  5029.5 1703.43
  5039.5 1704.94  5099.7 1709.84  5119.0 1712.76  5124.0 1712.91  5129.8 1714.69
  5139.9 1716.12  5170.0 1719.63  5190.2 1720.70  5210.1 1721.62  5237.2 1724.66
  5288.2 1728.19  5360.7 1730.99  5422.5 1731.78  5448.5 1732.06  5458.0 1732.29
#Mann=8,-1,0
  4030.0   0.035       0  4996.7   0.035       0  5002.1   0.035       0
  5015.5    0.07       0  5190.2   0.035       0  5288.2    0.07       0
  5422.5   0.035       0  5448.5    0.07       0
Bank Sta=4996.7,5002.1
Exp/Cntr=0.3,0.1

Type RM Length L Ch R = 1,15878,391,391,391
BEGIN DESCRIPTION:
Mapping XS eaae4f0e
END DESCRIPTION:
XS GIS Cut Line= 3
      1686098.00      6999160.07      1685775.07      7000061.15
      1685665.69      7000368.46
#Sta/Elev= 30
  4044.9 1721.74  4063.6 1721.59  4122.9 1716.99  4161.2 1713.00  4188.8 1712.14
  4304.4 1709.41  4340.4 1707.64  4396.6 1706.13  4458.1 1704.93  4514.3 1704.76
  4632.0 1701.31  4669.4 1699.24  4818.2 1698.07  4959.7 1699.50  4977.5 1698.59
  4997.5 1695.68  5006.6 1695.15  5007.1 1694.65  5012.1 1695.15  5015.9 1696.50
  5041.2 1701.01  5052.1 1704.05  5115.5 1710.30  5139.3 1714.25  5189.8 1719.83
  5195.6 1721.68  5206.3 1722.51  5232.3 1725.84  5257.3 1727.96  5328.3 1730.12
#Mann=7,-1,0
  4044.9   0.035       0  4122.9    0.07       0  4188.8   0.035       0
  4997.5    0.07       0  5006.6    0.07       0  5012.1    0.07       0
  5206.3   0.035       0
Bank Sta=5006.6,5012.1
Exp/Cntr=0.3,0.1

Type RM Length L Ch R = 1,15487,803,803,803
BEGIN DESCRIPTION:
Mapping XS ef903cfb
END DESCRIPTION:
XS GIS Cut Line= 3
      1686059.81      6999047.24      1685485.14      6999825.04
      1685327.14      7000057.70
#Sta/Elev= 30
  4037.4 1723.06  4073.4 1721.59  4099.3 1720.51  4134.8 1717.33  4191.1 1711.00
  4264.7 1707.93  4291.4 1706.64  4446.2 1703.23  4473.4 1702.60  4677.6 1697.82
  4757.0 1695.05  4775.1 1693.60  4775.5 1693.10  4780.6 1693.60  4834.1 1695.61
  4921.1 1697.34  4957.4 1696.60  4984.5 1693.76  4992.9 1694.31  5003.2 1696.65
  5009.0 1696.65  5013.8 1699.06  5034.8 1702.29  5064.7 1705.69  5106.7 1712.41
  5157.6 1716.05  5178.6 1718.97  5232.5 1723.84  5274.9 1725.19  5285.7 1725.88
#Mann=9,-1,0
  4037.4   0.035       0  4073.4    0.07       0  4264.7   0.035       0
  4446.2    0.07       0  4473.4   0.035       0  4775.1   0.035       0
  4780.6   0.035       0  5232.5    0.07       0  5274.9   0.035       0
Bank Sta=4775.1,4780.6
Exp/Cntr=0.3,0.1

Type RM Length L Ch R = 1,14684,125,125,125
BEGIN DESCRIPTION:
Mapping XS 69986507
END DESCRIPTION:
XS GIS Cut Line= 4
      1685923.82      6998932.00      1685620.03      6999043.10
      1685545.38      6999091.71      1685108.92      6999436.38
#Sta/Elev= 30
  4589.0 1720.91  4641.0 1717.89  4715.5 1709.91  4755.1 1706.53  4780.5 1704.85
  4871.9 1699.56  4912.3 1697.51  4933.5 1694.61  4942.3 1691.54  4948.6 1688.12
  4954.1 1687.33  4963.8 1683.97  4978.1 1681.00  4988.0 1680.94  4988.5 1680.44
  4993.6 1680.94  5049.3 1681.05  5063.8 1682.75  5105.4 1692.52  5152.1 1693.23
  5248.1 1693.40  5262.5 1691.94  5277.0 1693.41  5341.1 1693.82  5370.0 1695.33
  5376.3 1696.11  5390.8 1699.71  5426.0 1702.67  5554.9 1705.84  5557.7 1705.83
#Mann=9,-1,0
  4589.0    0.07       0  4755.1   0.035       0  4780.5    0.07       0
  4871.9   0.035       0  4954.1    0.07       0  4988.0    0.07       0
  4993.6    0.07       0  5152.1   0.035       0  5554.9    0.07       0
Bank Sta=4988,4993.6
Exp/Cntr=0.3,0.1

Type RM Length L Ch R = 1,14559,68,68,68
BEGIN DESCRIPTION:
Mapping XS 3dd40741
END DESCRIPTION:
XS GIS Cut Line= 4
      1685810.99      6998890.33      1685585.31      6998982.33
      1685429.06      6999063.93      1685124.11      6999313.43
#Sta/Elev= 30
  4581.0 1717.59  4609.3 1714.79  4625.1 1711.94  4733.3 1702.02  4844.9 1700.21
  4850.5 1697.72  4867.0 1698.93  4872.6 1695.55  4889.0 1696.95  4894.7 1693.61
  4911.1 1696.58  4916.8 1693.61  4933.2 1696.92  4938.3 1694.92  4955.3 1699.99
  4960.9 1697.28  4971.7 1699.13  5001.9 1698.69  5020.5 1697.89  5028.4 1694.13
  5034.8 1695.18  5042.7 1692.35  5079.6 1692.72  5098.7 1695.08  5182.0 1691.29
  5182.5 1690.79  5187.6 1691.29  5240.8 1693.25  5312.6 1701.80  5395.0 1704.56
#Mann=9,-1,0
  4581.0   0.035       0  4609.3    0.07       0  4625.1   0.035       0
  4733.3    0.07       0  4938.3   0.035       0  5001.9    0.07       0
  5079.6   0.035       0  5182.0   0.035       0  5187.6   0.035       0
Bank Sta=5182,5187.6
Exp/Cntr=0.3,0.1

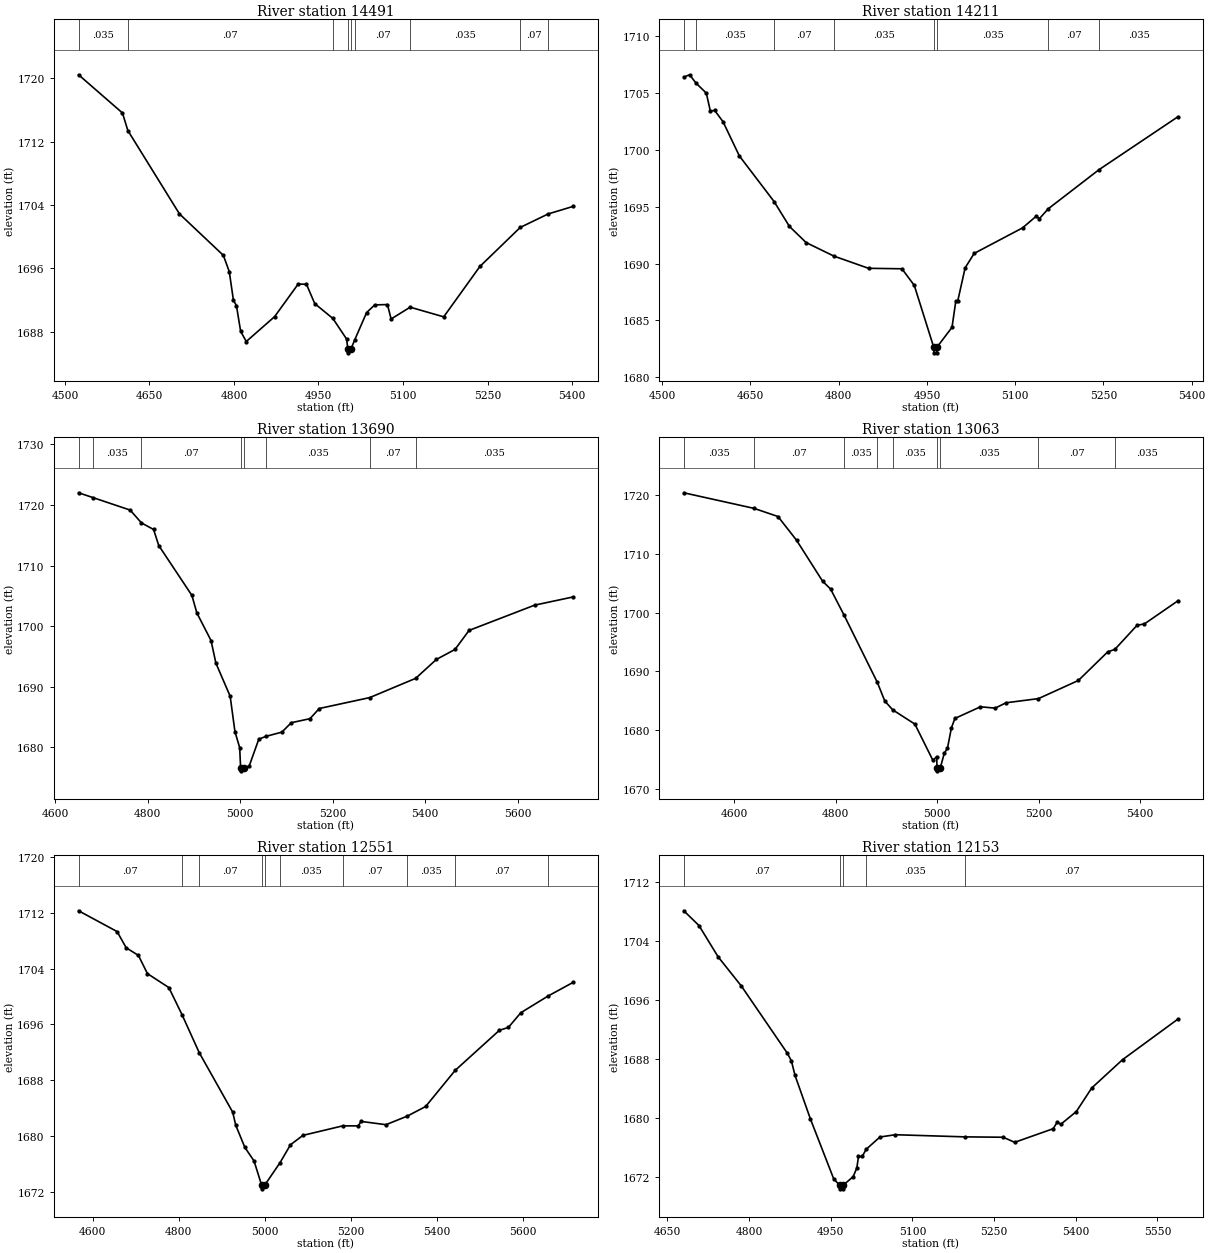
Type RM Length L Ch R = 1,14491,280,280,280
BEGIN DESCRIPTION:
Mapping XS 3d0a0a66
END DESCRIPTION:
XS GIS Cut Line= 4
      1685809.29      6998817.39      1685531.49      6998907.68
      1685376.98      6999018.79      1685064.44      6999260.14
#Sta/Elev= 30
  4524.3 1720.42  4602.2 1715.60  4611.7 1713.39  4703.3 1702.87  4781.2 1697.64
  4791.7 1695.59  4799.1 1691.97  4804.4 1691.31  4811.9 1688.05  4821.9 1686.77
  4872.2 1689.91  4914.0 1694.02  4928.7 1693.99  4943.4 1691.55  4975.5 1689.68
  4999.9 1687.08  5002.1 1685.84  5002.5 1685.34  5007.7 1685.84  5014.6 1687.02
  5035.4 1690.42  5049.9 1691.39  5072.4 1691.43  5078.9 1689.61  5112.7 1691.10
  5172.2 1689.88  5236.5 1696.24  5308.0 1701.16  5357.5 1702.86  5401.6 1703.81
#Mann=9,-1,0
  4524.3   0.035       0  4611.7    0.07       0  4975.5   0.035       0
  5002.1   0.035       0  5007.7   0.035       0  5014.6    0.07       0
  5112.7   0.035       0  5308.0    0.07       0  5357.5   0.035       0
Bank Sta=5002.1,5007.7
Exp/Cntr=0.3,0.1

Type RM Length L Ch R = 1,14211,521,521,521
BEGIN DESCRIPTION:
Mapping XS 60fd4d94
END DESCRIPTION:
XS GIS Cut Line= 3
      1685469.50      6998538.73      1685155.71      6998882.46
      1685000.18      6999223.34
#Sta/Elev= 30
  4536.9 1706.37  4546.8 1706.57  4557.7 1705.84  4575.2 1704.96  4582.0 1703.39
  4589.4 1703.44  4603.6 1702.45  4631.3 1699.45  4690.4 1695.44  4716.4 1693.26
  4744.8 1691.84  4792.1 1690.65  4850.9 1689.58  4907.6 1689.54  4928.6 1688.08
  4961.6 1682.66  4962.0 1682.16  4966.7 1682.16  4967.2 1682.66  4992.7 1684.40
  4999.1 1686.68  5002.3 1686.68  5015.0 1689.62  5030.4 1690.89  5112.6 1693.13
  5135.7 1694.15  5141.2 1693.94  5156.1 1694.80  5242.5 1698.24  5377.0 1702.90
#Mann=8,-1,0
  4536.9    0.07       0  4557.7   0.035       0  4690.4    0.07       0
  4792.1   0.035       0  4961.6   0.035       0  4967.2   0.035       0
  5156.1    0.07       0  5242.5   0.035       0
Bank Sta=4961.6,4967.2
Exp/Cntr=0.3,0.1

Type RM Length L Ch R = 1,13690,627,627,627
BEGIN DESCRIPTION:
Mapping XS f9f04ab8
END DESCRIPTION:
XS GIS Cut Line= 3
      1684709.96      6998259.59      1684795.03      6998603.34
      1684907.89      6999309.97
#Sta/Elev= 30
  4650.3 1722.01  4682.5 1721.19  4762.0 1719.15  4786.3 1717.04  4812.6 1715.95
  4823.8 1713.30  4895.5 1705.07  4906.2 1702.18  4936.9 1697.62  4947.4 1693.89
  4978.3 1688.42  4988.6 1682.60  4998.9 1679.93  5000.9 1676.61  5001.4 1676.11
  5007.5 1676.61  5019.3 1676.87  5040.2 1681.33  5055.2 1681.79  5090.2 1682.50
  5110.4 1684.05  5150.9 1684.72  5171.2 1686.40  5280.2 1688.20  5379.7 1691.38
  5424.3 1694.49  5464.8 1696.15  5495.2 1699.29  5637.0 1703.46  5720.0 1704.81
#Mann=8,-1,0
  4650.3    0.07       0  4682.5   0.035       0  4786.3    0.07       0
  5000.9    0.07       0  5007.5    0.07       0  5055.2   0.035       0
  5280.2    0.07       0  5379.7   0.035       0
Bank Sta=5000.9,5007.5
Exp/Cntr=0.3,0.1

Type RM Length L Ch R = 1,13063,512,512,512
BEGIN DESCRIPTION:
Mapping XS 930f0a8b
END DESCRIPTION:
XS GIS Cut Line= 3
      1684082.57      6998513.44      1684351.69      6998938.83
      1684625.99      6999320.77
#Sta/Elev= 30
  4501.0 1720.34  4639.4 1717.69  4686.5 1716.31  4723.0 1712.29  4774.7 1705.28
  4790.0 1704.01  4816.8 1699.53  4882.2 1688.13  4896.9 1684.96  4912.6 1683.46
  4956.1 1681.05  4991.6 1674.89  4999.3 1675.53  4999.5 1673.61  5000.0 1673.11
  5006.1 1673.61  5014.1 1676.12  5020.2 1676.92  5028.0 1680.40  5034.9 1682.01
  5085.3 1683.99  5114.2 1683.76  5135.6 1684.67  5199.5 1685.38  5278.1 1688.46
  5335.8 1693.31  5350.1 1693.75  5393.5 1697.82  5408.2 1698.07  5474.6 1702.02
#Mann=9,-1,0
  4501.0   0.035       0  4639.4    0.07       0  4816.8   0.035       0
  4882.2    0.07       0  4912.6   0.035       0  4999.5   0.035       0
  5006.1   0.035       0  5199.5    0.07       0  5350.1   0.035       0
Bank Sta=4999.5,5006.1
Exp/Cntr=0.3,0.1

Type RM Length L Ch R = 1,12551,398,398,398
BEGIN DESCRIPTION:
Mapping XS 0bf1fdc2
END DESCRIPTION:
XS GIS Cut Line= 3
      1683602.54      6998833.95      1683909.85      6999146.47
      1684343.89      6999708.98
#Sta/Elev= 30
  4567.2 1712.31  4656.7 1709.33  4677.9 1707.00  4706.2 1705.91  4727.3 1703.29
  4776.9 1701.30  4807.8 1697.38  4847.4 1691.98  4925.3 1683.43  4932.5 1681.54
  4953.6 1678.37  4974.9 1676.43  4992.7 1672.93  4993.2 1672.43  4999.4 1672.93
  5034.9 1676.14  5059.6 1678.75  5088.6 1680.10  5180.9 1681.46  5217.2 1681.46
  5223.5 1682.10  5281.5 1681.63  5331.0 1682.86  5373.7 1684.24  5442.3 1689.42
  5545.1 1695.17  5565.9 1695.58  5594.9 1697.69  5658.3 1700.09  5716.0 1702.03
#Mann=10,-1,0
  4567.2    0.07       0  4807.8   0.035       0  4847.4    0.07       0
  4992.7    0.07       0  4999.4    0.07       0  5034.9   0.035       0
  5180.9    0.07       0  5331.0   0.035       0  5442.3    0.07       0
  5658.3   0.035       0
Bank Sta=4992.7,4999.4
Exp/Cntr=0.3,0.1

Type RM Length L Ch R = 1,12153,301,301,301
BEGIN DESCRIPTION:
Mapping XS 380aeed0
END DESCRIPTION:
XS GIS Cut Line= 3
      1683364.33      6999169.64      1683603.92      6999387.09
      1684024.35      6999793.21
#Sta/Elev= 30
  4680.0 1708.10  4707.9 1706.10  4743.1 1701.85  4785.7 1697.90  4870.1 1688.79
  4877.6 1687.75  4884.3 1685.78  4912.7 1679.84  4955.3 1671.75  4966.1 1670.88
  4966.6 1670.38  4972.4 1670.38  4972.9 1670.88  4991.1 1672.03  4997.9 1673.22
  5000.9 1674.77  5007.8 1674.77  5014.8 1675.73  5040.3 1677.41  5068.6 1677.72
  5196.4 1677.43  5266.7 1677.38  5287.8 1676.69  5358.6 1678.54  5365.8 1679.42
  5372.7 1679.15  5401.0 1680.86  5429.3 1684.06  5485.9 1687.90  5588.1 1693.43
#Mann=5,-1,0
  4680.0    0.07       0  4966.1    0.07       0  4972.9    0.07       0
  5014.8   0.035       0  5196.4    0.07       0
Bank Sta=4966.1,4972.9
Exp/Cntr=0.3,0.1

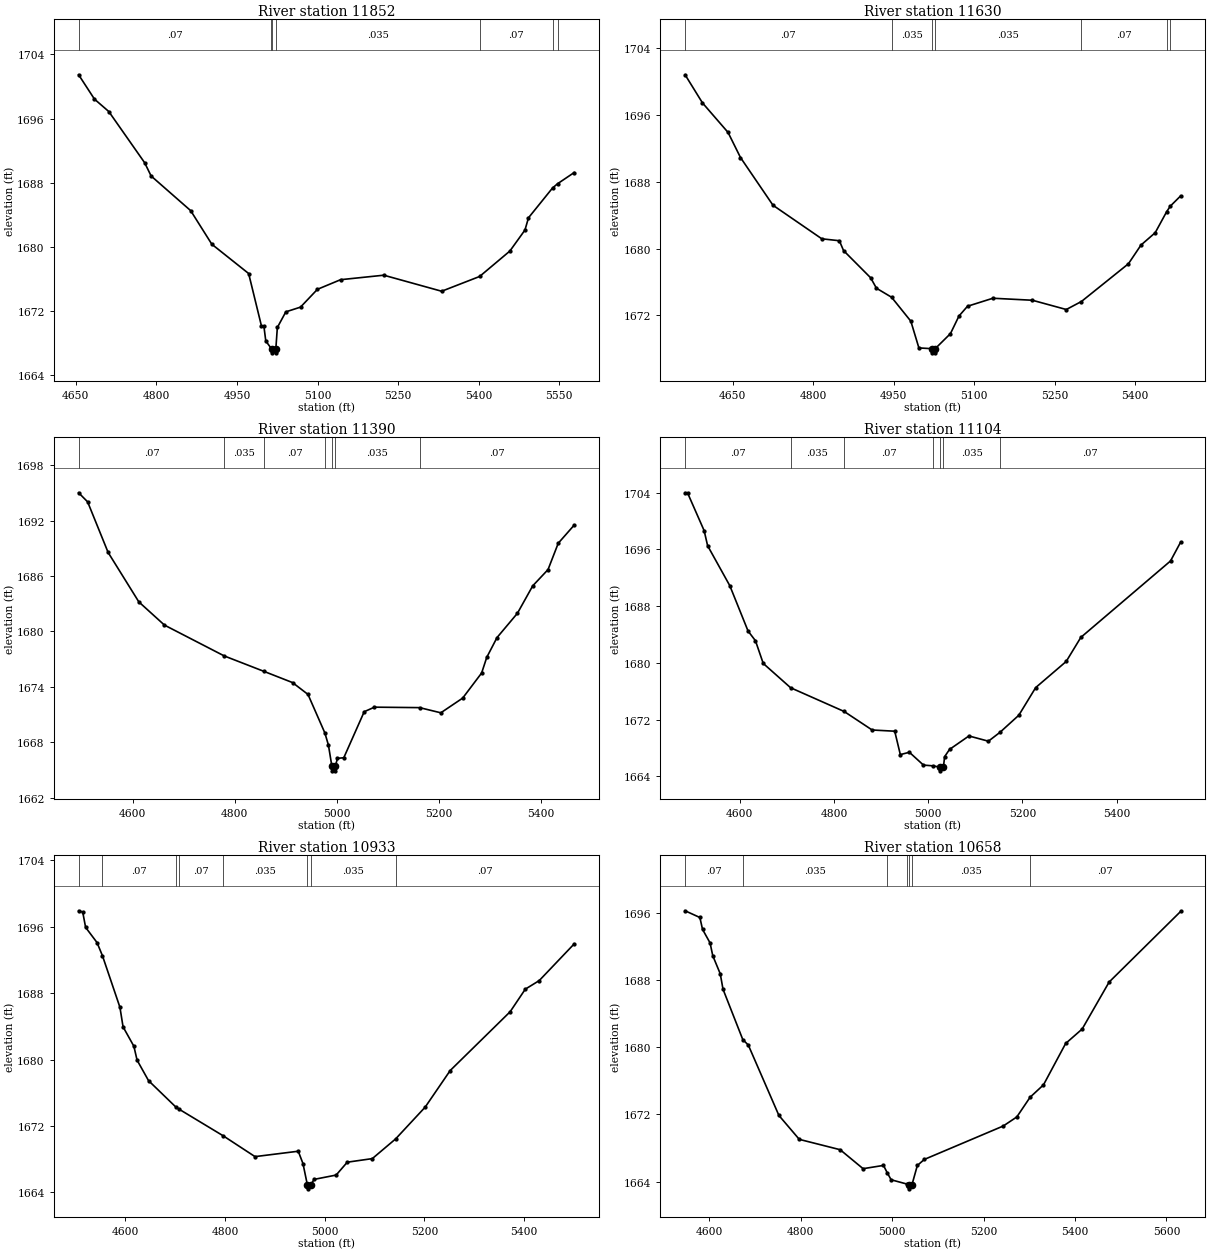
Type RM Length L Ch R = 1,11852,222,222,222
BEGIN DESCRIPTION:
Mapping XS ef8ce564
END DESCRIPTION:
XS GIS Cut Line= 3
      1683076.56      6999497.77      1683408.60      6999590.22
      1683908.59      6999879.27
#Sta/Elev= 30
  4655.4 1701.46  4684.9 1698.42  4711.5 1696.88  4778.3 1690.49  4790.3 1688.84
  4863.9 1684.52  4903.3 1680.33  4971.8 1676.68  4995.6 1670.15  5000.1 1670.15
  5003.7 1668.27  5013.7 1667.35  5015.6 1667.29  5016.1 1666.79  5021.9 1666.79
  5022.4 1667.29  5025.2 1669.95  5041.0 1671.90  5068.3 1672.49  5099.8 1674.71
  5142.9 1675.91  5223.3 1676.47  5331.0 1674.47  5401.6 1676.31  5457.9 1679.48
  5486.0 1682.10  5492.6 1683.63  5537.3 1687.34  5546.6 1687.87  5577.6 1689.27
#Mann=7,-1,0
  4655.4    0.07       0  5013.7   0.035       0  5015.6    0.07       0
  5022.4   0.035       0  5401.6    0.07       0  5537.3   0.035       0
  5546.6    0.07       0
Bank Sta=5015.6,5022.4
Exp/Cntr=0.3,0.1

Type RM Length L Ch R = 1,11630,240,240,240
BEGIN DESCRIPTION:
Mapping XS 5710397f
END DESCRIPTION:
XS GIS Cut Line= 3
      1682922.97      6999730.85      1683357.82      6999795.95
      1683817.45      6999946.99
#Sta/Elev= 30
  4561.3 1700.83  4593.7 1697.46  4641.3 1693.93  4664.5 1690.92  4725.1 1685.20
  4816.1 1681.18  4848.8 1680.95  4856.6 1679.77  4907.1 1676.51  4917.9 1675.26
  4946.1 1674.18  4982.0 1671.31  4997.0 1668.11  5020.6 1668.02  5021.1 1667.52
  5026.9 1667.52  5027.4 1668.02  5055.8 1669.82  5071.7 1671.93  5087.6 1673.10
  5134.9 1674.06  5208.5 1673.82  5271.7 1672.71  5299.9 1673.67  5387.5 1678.19
  5410.9 1680.43  5437.4 1681.91  5458.6 1684.41  5465.5 1685.09  5484.8 1686.32
#Mann=7,-1,0
  4561.3    0.07       0  4946.1   0.035       0  5020.6   0.035       0
  5027.4   0.035       0  5299.9    0.07       0  5458.6   0.035       0
  5465.5    0.07       0
Bank Sta=5020.6,5027.4
Exp/Cntr=0.3,0.1

Type RM Length L Ch R = 1,11390,286,286,286
BEGIN DESCRIPTION:
Mapping XS 5620bad8
END DESCRIPTION:
XS GIS Cut Line= 3
      1682847.44      7000081.10      1683355.22      7000035.53
      1683816.18      7000049.85
#Sta/Elev= 30
  4494.0 1695.00  4511.6 1694.02  4551.8 1688.54  4612.0 1683.19  4662.2 1680.68
  4779.5 1677.34  4857.3 1675.67  4913.2 1674.46  4943.4 1673.18  4976.5 1669.01
  4983.5 1667.69  4990.2 1665.41  4990.7 1664.91  4996.5 1664.91  4997.0 1665.41
  5001.2 1666.26  5013.6 1666.33  5053.6 1671.31  5073.6 1671.80  5162.1 1671.75
  5203.7 1671.19  5246.5 1672.78  5283.7 1675.50  5293.7 1677.19  5313.8 1679.33
  5353.8 1681.96  5383.8 1684.93  5413.8 1686.69  5433.8 1689.54  5465.0 1691.50
#Mann=7,-1,0
  4494.0    0.07       0  4779.5   0.035       0  4857.3    0.07       0
  4976.5   0.035       0  4990.2   0.035       0  4997.0   0.035       0
  5162.1    0.07       0
Bank Sta=4990.2,4997
Exp/Cntr=0.3,0.1

Type RM Length L Ch R = 1,11104,171,171,171
BEGIN DESCRIPTION:
Mapping XS d2a8f9cf
END DESCRIPTION:
XS GIS Cut Line= 3
      1682870.43      7000476.91      1683353.08      7000289.41
      1683870.23      7000157.52
#Sta/Elev= 30
  4484.1 1703.99  4489.2 1703.99  4524.5 1698.65  4531.9 1696.52  4579.0 1690.88
  4617.7 1684.49  4633.4 1683.12  4649.9 1679.92  4708.0 1676.49  4821.7 1673.14
  4881.0 1670.53  4928.9 1670.36  4940.8 1667.06  4960.0 1667.39  4989.9 1665.58
  5010.9 1665.47  5025.3 1665.27  5025.8 1664.77  5032.2 1665.27  5034.8 1666.77
  5045.2 1667.79  5086.4 1669.69  5127.7 1668.95  5152.4 1670.21  5192.2 1672.61
  5228.0 1676.51  5292.8 1680.20  5323.8 1683.59  5514.1 1694.37  5535.6 1697.03
#Mann=7,-1,0
  4484.1    0.07       0  4708.0   0.035       0  4821.7    0.07       0
  5010.9   0.035       0  5025.3    0.07       0  5032.2   0.035       0
  5152.4    0.07       0
Bank Sta=5025.3,5032.2
Exp/Cntr=0.3,0.1

Type RM Length L Ch R = 1,10933,275,275,275
BEGIN DESCRIPTION:
Mapping XS 323b05cf
END DESCRIPTION:
XS GIS Cut Line= 3
      1682972.84      7000687.00      1683405.16      7000443.92
      1683849.64      7000219.94
#Sta/Elev= 30
  4506.6 1697.93  4514.8 1697.78  4520.6 1695.93  4543.5 1694.10  4554.4 1692.51
  4589.4 1686.31  4595.7 1683.95  4617.4 1681.61  4623.8 1679.94  4646.8 1677.47
  4701.4 1674.30  4708.4 1674.02  4796.4 1670.83  4860.3 1668.32  4947.0 1668.97
  4956.5 1667.48  4965.2 1664.94  4965.7 1664.44  4972.1 1664.94  4978.9 1665.58
  5023.0 1666.10  5045.3 1667.65  5095.5 1668.08  5142.2 1670.45  5201.5 1674.28
  5251.7 1678.69  5371.9 1685.77  5402.3 1688.49  5430.2 1689.52  5500.3 1693.94
#Mann=8,-1,0
  4506.6   0.035       0  4554.4    0.07       0  4701.4   0.035       0
  4708.4    0.07       0  4796.4   0.035       0  4965.2   0.035       0
  4972.1   0.035       0  5142.2    0.07       0
Bank Sta=4965.2,4972.1
Exp/Cntr=0.3,0.1

Type RM Length L Ch R = 1,10658,261,261,261
BEGIN DESCRIPTION:
Mapping XS cc685b2f
END DESCRIPTION:
XS GIS Cut Line= 3
      1683051.00      7000907.46      1683457.24      7000702.60
      1683986.79      7000364.04
#Sta/Elev= 30
  4547.5 1696.25  4579.8 1695.45  4585.6 1694.04  4602.1 1692.42  4608.0 1690.90
  4624.4 1688.74  4630.4 1686.91  4673.6 1680.92  4685.7 1680.26  4752.6 1671.88
  4797.2 1669.03  4886.5 1667.80  4936.7 1665.54  4981.3 1665.93  4989.4 1665.06
  4998.0 1664.22  5032.5 1663.71  5036.6 1663.64  5037.1 1663.14  5043.6 1663.64
  5055.3 1665.92  5070.5 1666.64  5243.1 1670.62  5272.8 1671.70  5301.9 1674.05
  5331.1 1675.52  5379.6 1680.45  5415.7 1682.17  5474.6 1687.76  5631.0 1696.17
#Mann=7,-1,0
  4547.5    0.07       0  4673.6   0.035       0  4989.4    0.07       0
  5032.5   0.035       0  5036.6    0.07       0  5043.6   0.035       0
  5301.9    0.07       0
Bank Sta=5036.6,5043.6
Exp/Cntr=0.3,0.1