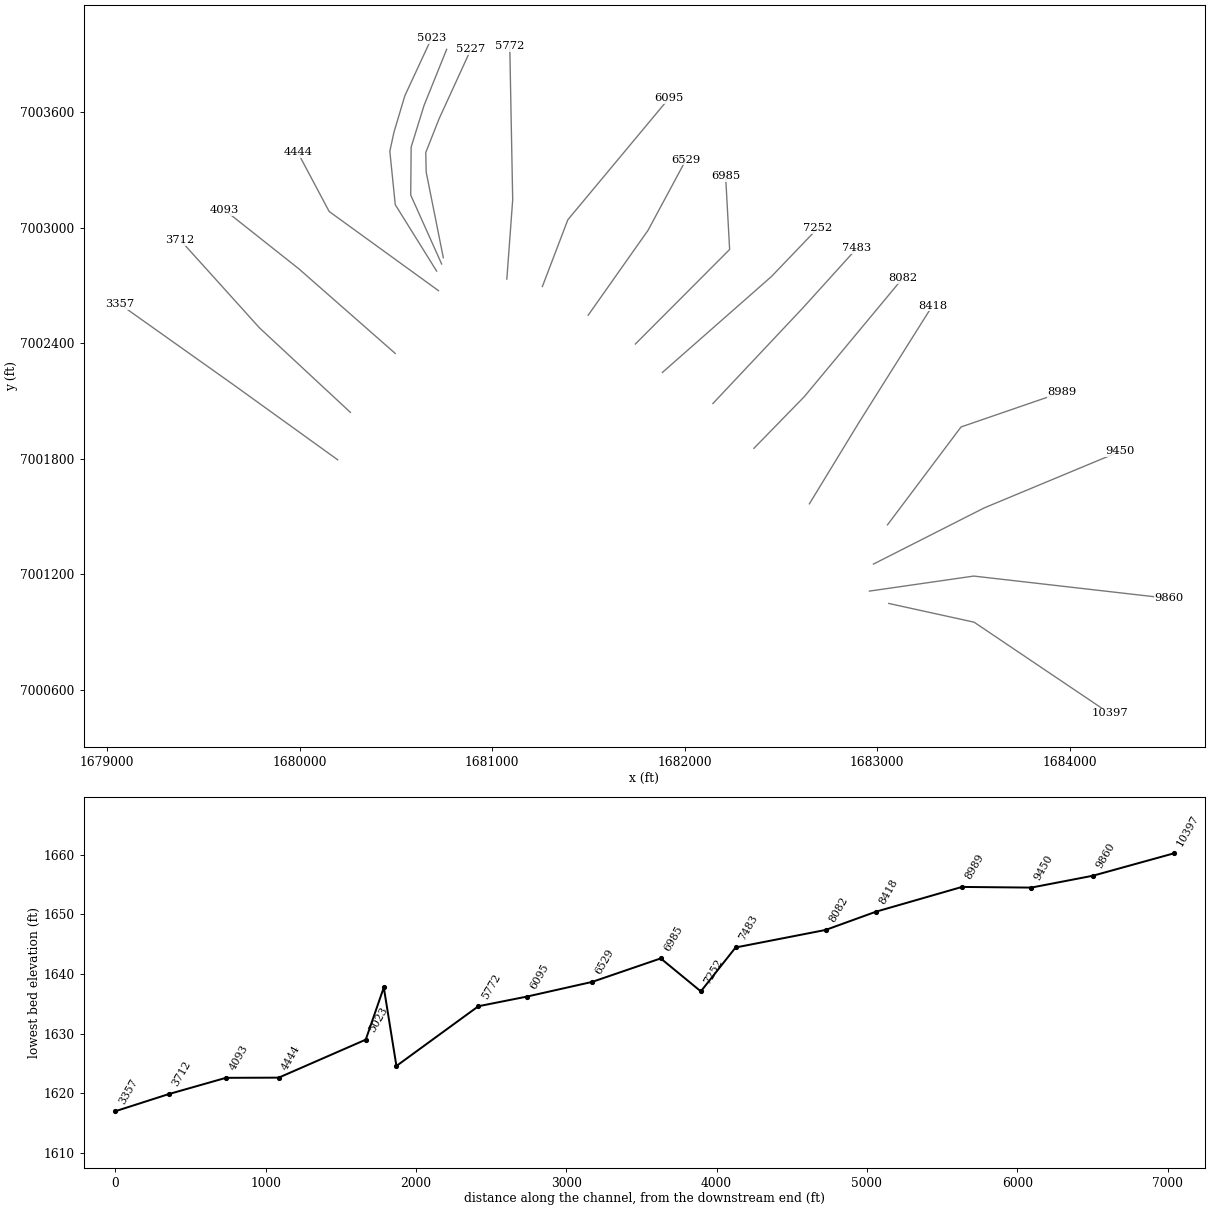
HEC-RAS study Chimney Creek 1169.prj: Chimney Creek 1169 Base Level Engineering

--- Chimney Creek 1169.g01 (geometry) --- (continued)

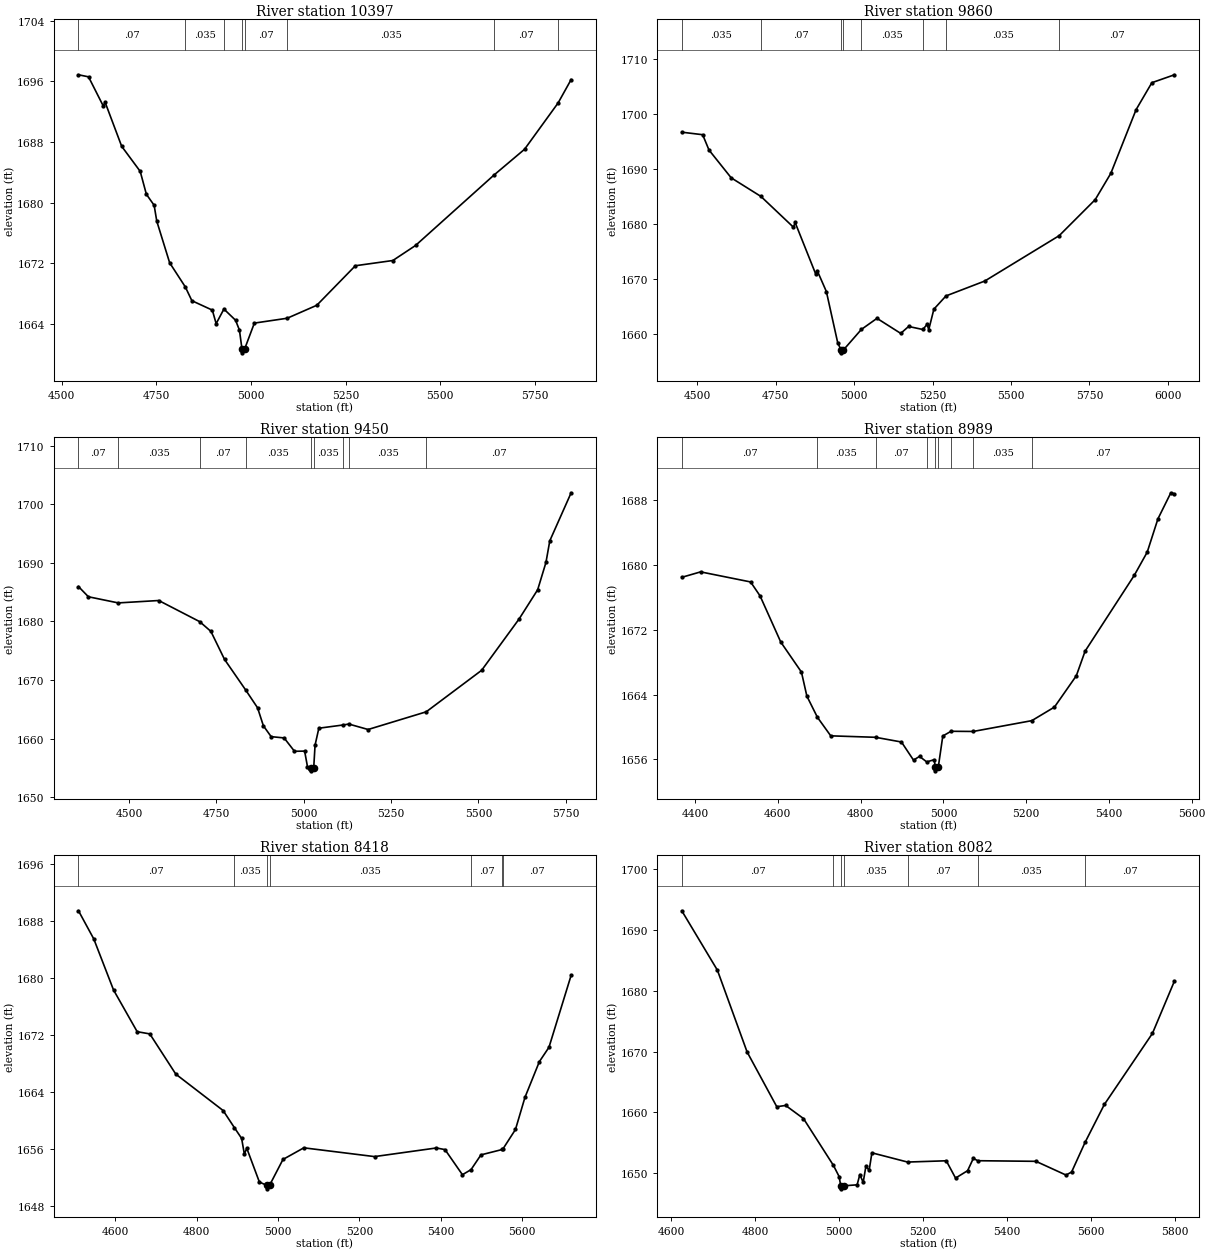
Type RM Length L Ch R = 1,10397,537,537,537
BEGIN DESCRIPTION:
Mapping XS f1ff740a
END DESCRIPTION:
XS GIS Cut Line= 3
      1683059.83      7001047.75      1683502.56      7000950.52
      1684205.66      7000476.58
#Sta/Elev= 30
  4544.2 1696.87  4570.7 1696.60  4609.4 1692.78  4614.5 1693.25  4658.3 1687.44
  4707.2 1684.14  4723.5 1681.12  4744.0 1679.67  4751.0 1677.57  4785.0 1672.09
  4826.3 1668.91  4843.7 1667.09  4897.7 1665.85  4907.8 1664.07  4928.3 1665.99
  4959.0 1664.52  4969.3 1663.22  4976.0 1660.72  4976.5 1660.22  4983.0 1660.72
  5008.7 1664.14  5095.4 1664.78  5173.6 1666.49  5275.5 1671.70  5374.5 1672.39
  5434.4 1674.37  5641.3 1683.64  5722.3 1687.05  5811.0 1693.16  5845.4 1696.24
#Mann=8,-1,0
  4544.2    0.07       0  4826.3   0.035       0  4928.3    0.07       0
  4976.0    0.07       0  4983.0    0.07       0  5095.4   0.035       0
  5641.3    0.07       0  5811.0   0.035       0
Bank Sta=4976,4983
Exp/Cntr=0.3,0.1

Type RM Length L Ch R = 1,9860,410,410,410
BEGIN DESCRIPTION:
Mapping XS 731dda04
END DESCRIPTION:
XS GIS Cut Line= 3
      1682959.16      7001111.98      1683500.82      7001190.10
      1684516.42      7001073.79
#Sta/Elev= 30
  4451.2 1696.65  4517.7 1696.19  4537.9 1693.40  4608.6 1688.34  4703.4 1684.95
  4807.1 1679.34  4812.2 1680.22  4877.5 1670.88  4882.6 1671.45  4911.8 1667.64
  4947.9 1658.33  4958.7 1656.98  4959.2 1656.48  4965.8 1656.98  5023.3 1660.74
  5073.1 1662.76  5148.7 1660.02  5173.8 1661.28  5219.1 1660.73  5232.9 1661.67
  5237.9 1660.68  5254.3 1664.43  5292.9 1666.84  5416.4 1669.55  5653.5 1677.81
  5768.3 1684.37  5818.0 1689.15  5898.5 1700.75  5948.8 1705.66  6020.7 1707.10
#Mann=8,-1,0
  4451.2   0.035       0  4703.4    0.07       0  4958.7    0.07       0
  4965.8    0.07       0  5023.3   0.035       0  5219.1    0.07       0
  5292.9   0.035       0  5653.5    0.07       0
Bank Sta=4958.7,4965.8
Exp/Cntr=0.3,0.1

Type RM Length L Ch R = 1,9450,461,461,461
BEGIN DESCRIPTION:
Mapping XS 968796af
END DESCRIPTION:
XS GIS Cut Line= 3
      1682980.20      7001252.45      1683554.81      7001544.10
      1684261.53      7001838.56
#Sta/Elev= 30
  4355.4 1685.96  4383.8 1684.22  4469.2 1683.17  4585.1 1683.58  4702.3 1679.97
  4734.3 1678.31  4773.3 1673.53  4833.5 1668.33  4867.9 1665.26  4884.6 1662.18
  4906.8 1660.33  4943.9 1660.11  4973.6 1657.83  5002.6 1657.86  5010.8 1655.20
  5021.4 1654.99  5021.9 1654.49  5028.6 1654.99  5032.5 1658.88  5043.3 1661.77
  5111.4 1662.31  5129.1 1662.48  5184.3 1661.55  5350.6 1664.57  5509.2 1671.66
  5616.5 1680.43  5669.6 1685.42  5693.3 1690.08  5704.3 1693.78  5765.4 1701.98
#Mann=9,-1,0
  4355.4    0.07       0  4469.2   0.035       0  4702.3    0.07       0
  4833.5   0.035       0  5021.4   0.035       0  5028.6   0.035       0
  5111.4    0.07       0  5129.1   0.035       0  5350.6    0.07       0
Bank Sta=5021.4,5028.6
Exp/Cntr=0.3,0.1

Type RM Length L Ch R = 1,8989,571,571,571
BEGIN DESCRIPTION:
Mapping XS 98295dda
END DESCRIPTION:
XS GIS Cut Line= 3
      1683052.92      7001456.28      1683434.85      7001964.93
      1683959.15      7002145.48
#Sta/Elev= 30
  4367.8 1678.43  4413.3 1679.10  4534.1 1677.86  4557.0 1676.14  4607.0 1670.46
  4657.0 1666.76  4670.1 1663.80  4695.5 1661.20  4727.8 1658.91  4836.1 1658.73
  4898.7 1658.15  4927.8 1655.92  4942.4 1656.38  4959.7 1655.70  4977.8 1655.97
  4980.4 1655.10  4980.9 1654.60  4987.8 1655.10  4998.6 1658.89  5018.5 1659.47
  5072.1 1659.45  5213.7 1660.78  5268.4 1662.45  5321.3 1666.31  5342.5 1669.34
  5461.4 1678.68  5492.6 1681.53  5518.5 1685.63  5549.7 1688.84  5558.4 1688.71
#Mann=9,-1,0
  4367.8    0.07       0  4695.5   0.035       0  4836.1    0.07       0
  4959.7   0.035       0  4980.4   0.035       0  4987.8   0.035       0
  5018.5    0.07       0  5072.1   0.035       0  5213.7    0.07       0
Bank Sta=4980.4,4987.8
Exp/Cntr=0.3,0.1

Type RM Length L Ch R = 1,8418,336,336,336
BEGIN DESCRIPTION:
Mapping XS bc35924b
END DESCRIPTION:
XS GIS Cut Line= 3
      1682647.51      7001565.66      1682904.47      7001987.56
      1683285.72      7002594.10
#Sta/Elev= 30
  4509.6 1689.44  4547.2 1685.49  4595.7 1678.34  4653.8 1672.49  4684.8 1672.18
  4748.7 1666.54  4864.9 1661.44  4892.6 1659.04  4910.4 1657.53  4917.2 1655.31
  4923.0 1656.16  4954.0 1651.42  4971.6 1650.96  4972.1 1650.46  4979.1 1650.96
  5012.0 1654.58  5063.2 1656.21  5237.0 1654.98  5388.9 1656.19  5410.1 1655.96
  5452.9 1652.44  5474.0 1653.15  5498.4 1655.22  5551.0 1655.98  5552.4 1656.05
  5583.2 1658.78  5606.5 1663.28  5641.9 1668.29  5665.5 1670.30  5720.0 1680.40
#Mann=7,-1,0
  4509.6    0.07       0  4892.6   0.035       0  4971.6   0.035       0
  4979.1   0.035       0  5474.0    0.07       0  5551.0   0.035       0
  5552.4    0.07       0
Bank Sta=4971.6,4979.1
Exp/Cntr=0.3,0.1

Type RM Length L Ch R = 1,8082,599,599,599
BEGIN DESCRIPTION:
Mapping XS 6bd486d1
END DESCRIPTION:
XS GIS Cut Line= 3
      1682359.32      7001853.87      1682621.48      7002122.97
      1683130.94      7002736.41
#Sta/Elev= 30
  4625.5 1693.17  4710.3 1683.39  4781.0 1669.93  4851.7 1660.91  4872.8 1661.12
  4915.3 1658.96  4986.5 1651.26  5000.1 1649.42  5004.0 1647.89  5004.5 1647.39
  5011.5 1647.89  5043.0 1648.05  5049.5 1649.74  5057.4 1648.45  5063.9 1651.09
  5071.7 1650.45  5078.2 1653.32  5163.1 1651.80  5255.3 1652.01  5277.4 1649.16
  5306.1 1650.38  5319.7 1652.40  5330.4 1652.02  5468.8 1651.92  5540.4 1649.66
  5553.7 1650.16  5585.8 1655.04  5631.7 1661.28  5746.2 1672.98  5798.6 1681.60
#Mann=7,-1,0
  4625.5    0.07       0  4986.5   0.035       0  5004.0   0.035       0
  5011.5   0.035       0  5163.1    0.07       0  5330.4   0.035       0
  5585.8    0.07       0
Bank Sta=5004,5011.5
Exp/Cntr=0.3,0.1

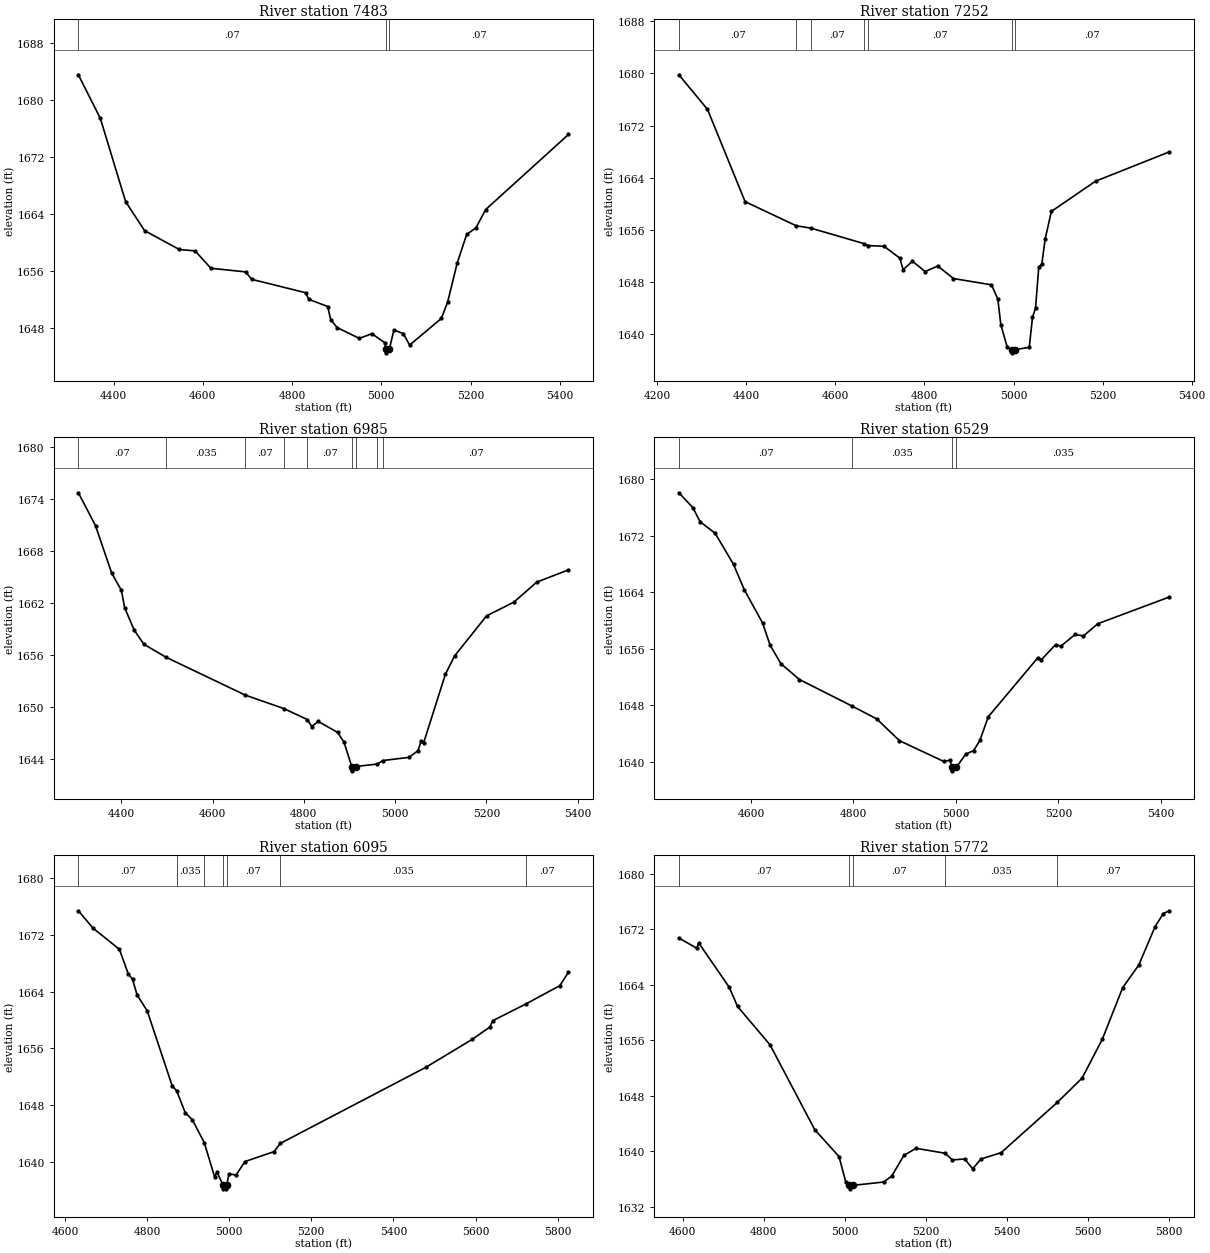
Type RM Length L Ch R = 1,7483,231,231,231
BEGIN DESCRIPTION:
Mapping XS 03914d9f
END DESCRIPTION:
XS GIS Cut Line= 3
      1682146.49      7002086.87      1682613.49      7002583.39
      1682892.99      7002892.40
#Sta/Elev= 30
  4321.1 1683.54  4370.4 1677.40  4427.0 1665.71  4469.5 1661.63  4547.2 1658.98
  4582.8 1658.78  4618.0 1656.34  4695.7 1655.83  4709.8 1654.78  4830.4 1652.90
  4837.3 1651.98  4879.8 1650.96  4886.6 1649.12  4900.8 1648.01  4950.6 1646.48
  4978.9 1647.14  5007.6 1645.87  5010.3 1644.95  5010.8 1644.45  5017.9 1644.95
  5028.3 1647.68  5049.4 1647.13  5063.4 1645.54  5134.4 1649.28  5148.6 1651.58
  5170.2 1657.11  5191.2 1661.09  5212.1 1662.03  5233.7 1664.59  5419.4 1675.15
#Mann=3,-1,0
  4321.1    0.07       0  5010.3    0.07       0  5017.9    0.07       0
Bank Sta=5010.3,5017.9
Exp/Cntr=0.3,0.1

Type RM Length L Ch R = 1,7252,267,267,267
BEGIN DESCRIPTION:
Mapping XS e844f7e1
END DESCRIPTION:
XS GIS Cut Line= 3
      1681884.34      7002248.33      1682450.30      7002746.58
      1682689.89      7002996.59
#Sta/Elev= 30
  4248.7 1679.80  4312.9 1674.49  4397.4 1660.31  4512.0 1656.61  4544.6 1656.25
  4664.7 1653.86  4673.4 1653.57  4709.5 1653.45  4744.6 1651.64  4752.2 1649.87
  4773.1 1651.17  4801.5 1649.57  4830.0 1650.43  4865.1 1648.50  4950.5 1647.54
  4964.7 1645.34  4971.4 1641.44  4985.6 1638.01  4995.8 1637.59  4996.3 1637.09
  5003.9 1637.59  5035.3 1637.94  5042.5 1642.53  5049.4 1643.99  5056.6 1650.24
  5063.6 1650.78  5070.8 1654.51  5084.9 1658.81  5184.0 1663.45  5349.0 1667.94
#Mann=7,-1,0
  4248.7    0.07       0  4512.0   0.035       0  4544.6    0.07       0
  4664.7   0.035       0  4673.4    0.07       0  4995.8    0.07       0
  5003.9    0.07       0
Bank Sta=4995.8,5003.9
Exp/Cntr=0.3,0.1

Type RM Length L Ch R = 1,6985,456,456,456
BEGIN DESCRIPTION:
Mapping XS aa3b4e7f
END DESCRIPTION:
XS GIS Cut Line= 3
      1681743.74      7002395.92      1682233.29      7002887.21
      1682212.45      7003267.38
#Sta/Elev= 30
  4305.8 1674.69  4343.5 1670.88  4378.9 1665.42  4400.1 1663.44  4407.2 1661.44
  4428.4 1658.83  4449.6 1657.21  4498.0 1655.72  4671.0 1651.37  4756.7 1649.79
  4807.5 1648.54  4817.3 1647.73  4831.4 1648.32  4873.8 1647.06  4888.0 1645.94
  4905.0 1643.12  4905.5 1642.62  4913.4 1643.12  4960.8 1643.40  4973.3 1643.81
  5030.2 1644.17  5050.2 1644.94  5057.3 1646.08  5062.3 1645.80  5110.3 1653.76
  5130.3 1655.86  5200.4 1660.49  5260.5 1662.08  5310.6 1664.39  5380.1 1665.80
#Mann=9,-1,0
  4305.8    0.07       0  4498.0   0.035       0  4671.0    0.07       0
  4756.7   0.035       0  4807.5    0.07       0  4905.0    0.07       0
  4913.4    0.07       0  4960.8   0.035       0  4973.3    0.07       0
Bank Sta=4905,4913.4
Exp/Cntr=0.3,0.1

Type RM Length L Ch R = 1,6529,434,434,434
BEGIN DESCRIPTION:
Mapping XS bcfc17da
END DESCRIPTION:
XS GIS Cut Line= 3
      1681498.73      7002545.70      1681809.50      7002986.69
      1682006.95      7003353.88
#Sta/Elev= 30
  4459.3 1678.09  4486.6 1675.99  4500.6 1674.00  4530.2 1672.34  4565.9 1667.94
  4586.8 1664.37  4622.5 1659.65  4637.3 1656.50  4658.2 1653.88  4694.6 1651.62
  4797.5 1647.85  4845.4 1646.04  4889.8 1642.95  4975.9 1640.02  4988.3 1640.18
  4992.3 1639.18  4992.8 1638.68  5000.7 1639.18  5019.1 1641.05  5034.3 1641.54
  5046.7 1642.99  5063.0 1646.34  5159.2 1654.66  5166.8 1654.44  5194.4 1656.57
  5204.7 1656.36  5232.6 1658.01  5248.8 1657.80  5276.4 1659.52  5415.7 1663.30
#Mann=4,-1,0
  4459.3    0.07       0  4797.5   0.035       0  4992.3   0.035       0
  5000.7   0.035       0
Bank Sta=4992.3,5000.7
Exp/Cntr=0.3,0.1

Type RM Length L Ch R = 1,6095,323,323,323
BEGIN DESCRIPTION:
Mapping XS 02f0412d
END DESCRIPTION:
XS GIS Cut Line= 3
      1681260.88      7002694.55      1681393.27      7003041.81
      1681919.24      7003673.84
#Sta/Elev= 30
  4632.6 1675.38  4668.4 1672.93  4732.6 1669.95  4754.0 1666.52  4764.7 1665.71
  4775.6 1663.54  4800.4 1661.27  4861.0 1650.75  4872.2 1650.00  4893.1 1646.91
  4910.0 1645.98  4939.2 1642.74  4964.8 1637.85  4970.2 1638.60  4985.2 1636.72
  4985.7 1636.22  4993.2 1636.22  4993.7 1636.72  4999.6 1638.34  5016.8 1638.16
  5038.3 1640.06  5109.2 1641.46  5124.3 1642.61  5478.9 1653.33  5592.2 1657.28
  5635.2 1659.02  5641.7 1659.89  5723.2 1662.27  5805.7 1664.85  5826.5 1666.74
#Mann=7,-1,0
  4632.6    0.07       0  4872.2   0.035       0  4939.2    0.07       0
  4985.2    0.07       0  4993.7    0.07       0  5124.3   0.035       0
  5723.2    0.07       0
Bank Sta=4985.2,4993.7
Exp/Cntr=0.3,0.1

Type RM Length L Ch R = 1,5772,545,545,545
BEGIN DESCRIPTION:
Mapping XS b412fcf3
END DESCRIPTION:
XS GIS Cut Line= 3
      1681076.43      7002733.62      1681106.81      7003145.98
      1681091.62      7003942.46
#Sta/Elev= 30
  4590.9 1670.74  4635.0 1669.27  4640.0 1670.02  4715.6 1663.61  4735.7 1660.88
  4815.9 1655.35  4926.2 1643.14  4986.3 1639.25  5002.9 1635.61  5012.1 1635.10
  5012.6 1634.60  5020.6 1635.10  5096.4 1635.58  5116.4 1636.44  5146.4 1639.41
  5176.4 1640.44  5247.9 1639.73  5266.4 1638.76  5296.4 1638.91  5316.4 1637.48
  5336.5 1638.90  5386.5 1639.81  5525.4 1647.06  5586.5 1650.56  5636.5 1656.17
  5686.5 1663.57  5726.5 1666.86  5766.5 1672.36  5786.5 1674.23  5801.0 1674.66
#Mann=5,-1,0
  4590.9    0.07       0  5012.1    0.07       0  5020.6    0.07       0
  5247.9   0.035       0  5525.4    0.07       0
Bank Sta=5012.1,5020.6
Exp/Cntr=0.3,0.1

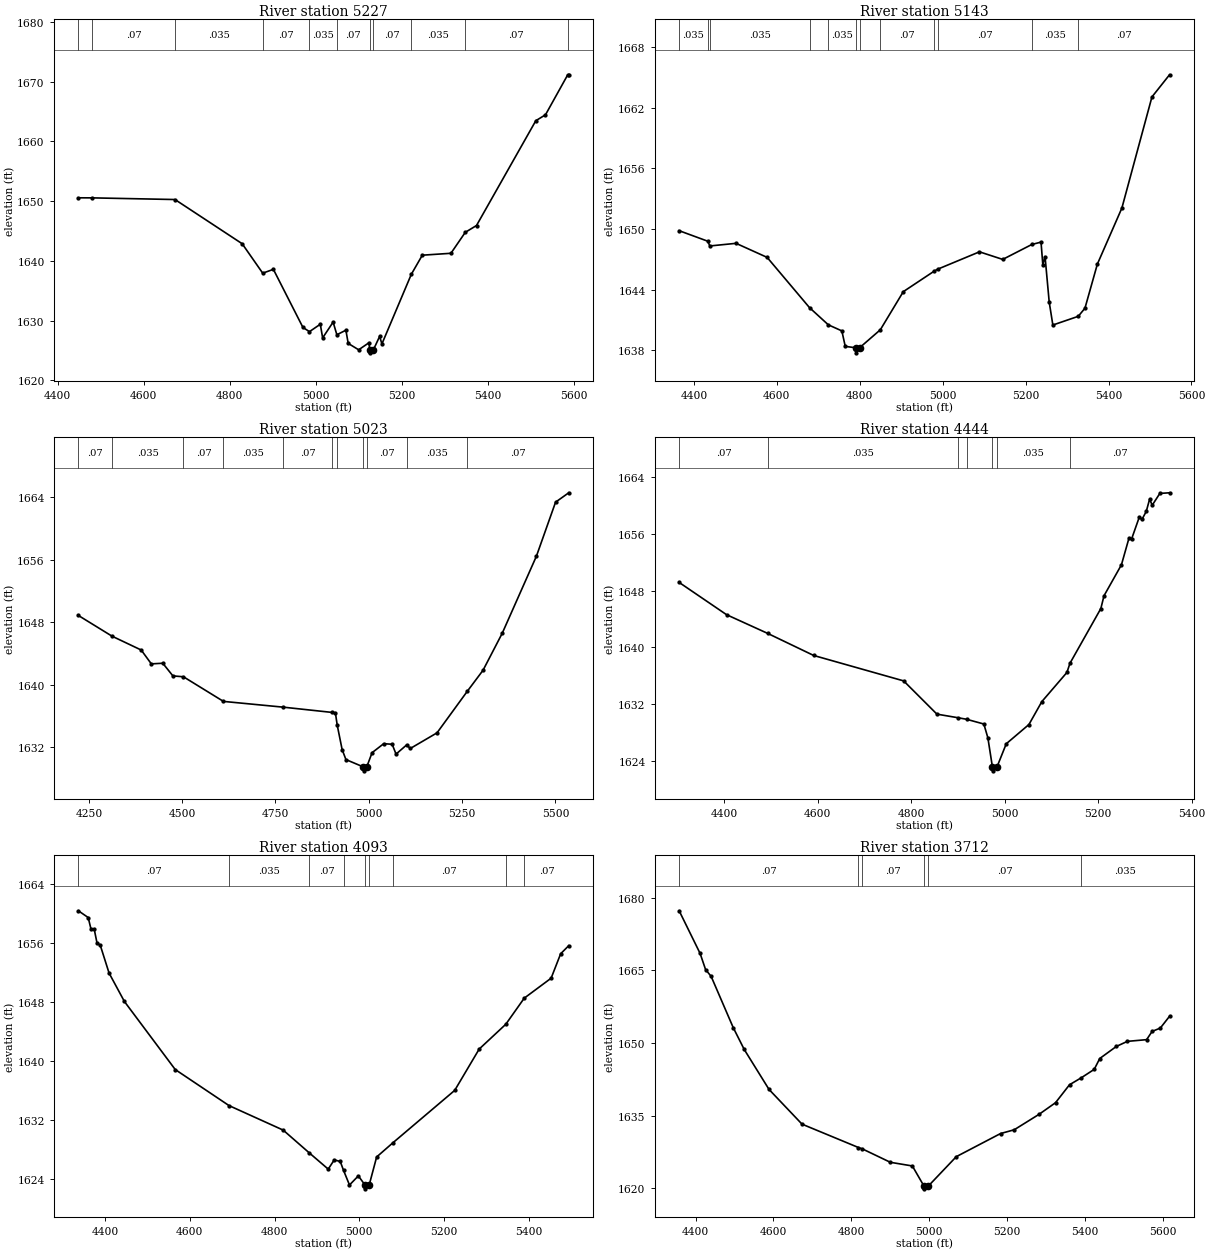
Type RM Length L Ch R = 1,5227,84,84,84
BEGIN DESCRIPTION:
Mapping XS eb83da60
END DESCRIPTION:
XS GIS Cut Line= 5
      1680746.57      7002844.31      1680657.59      7003289.21
      1680655.42      7003391.20      1680724.87      7003566.98
      1680889.78      7003927.20
#Sta/Elev= 30
  4447.9 1650.55  4479.8 1650.54  4672.7 1650.26  4829.0 1642.86  4876.8 1637.93
  4901.6 1638.57  4970.4 1628.84  4985.6 1628.14  5010.8 1629.38  5016.2 1627.09
  5040.6 1629.74  5049.3 1627.62  5070.3 1628.38  5075.7 1626.17  5100.0 1625.10
  5124.4 1626.30  5125.3 1625.09  5125.8 1624.59  5134.3 1625.09  5148.8 1627.35
  5154.1 1626.08  5222.6 1637.75  5248.1 1640.94  5314.7 1641.26  5348.1 1644.77
  5374.2 1645.91  5512.2 1663.46  5534.7 1664.45  5586.1 1671.10  5588.8 1671.15
#Mann=11,-1,0
  4447.9   0.035       0  4479.8    0.07       0  4672.7   0.035       0
  4876.8    0.07       0  4985.6   0.035       0  5049.3    0.07       0
  5125.3   0.035       0  5134.3    0.07       0  5222.6   0.035       0
  5348.1    0.07       0  5586.1   0.035       0
Bank Sta=5125.3,5134.3
Exp/Cntr=0.3,0.1

Type RM Length L Ch R = 1,5143,120,120,120
BEGIN DESCRIPTION:
Mapping XS 39fb0416
END DESCRIPTION:
XS GIS Cut Line= 5
      1680737.89      7002811.77      1680577.30      7003169.85
      1680579.47      7003419.41      1680646.74      7003636.43
      1680763.91      7003927.19
#Sta/Elev= 30
  4364.4 1649.83  4433.4 1648.79  4438.4 1648.32  4501.6 1648.58  4576.6 1647.19
  4678.8 1642.22  4724.2 1640.52  4756.8 1639.92  4765.0 1638.39  4790.5 1638.25
  4791.0 1637.75  4799.5 1638.25  4849.6 1640.03  4905.0 1643.80  4979.2 1645.82
  4987.8 1646.02  5088.7 1647.74  5144.8 1646.99  5215.2 1648.47  5237.2 1648.70
  5241.5 1646.46  5246.9 1647.26  5256.9 1642.78  5265.7 1640.50  5326.9 1641.36
  5343.1 1642.16  5373.1 1646.53  5432.2 1652.07  5504.7 1663.06  5547.1 1665.25
#Mann=12,-1,0
  4364.4   0.035       0  4433.4    0.07       0  4438.4   0.035       0
  4678.8    0.07       0  4724.2   0.035       0  4790.5    0.07       0
  4799.5   0.035       0  4849.6    0.07       0  4979.2   0.035       0
  4987.8    0.07       0  5215.2   0.035       0  5326.9    0.07       0
Bank Sta=4790.5,4799.5
Exp/Cntr=0.3,0.1

Type RM Length L Ch R = 1,5023,579,579,579
BEGIN DESCRIPTION:
Mapping XS 9b5c1155
END DESCRIPTION:
XS GIS Cut Line= 6
      1680711.87      7002774.85      1680497.00      7003119.93
      1680468.79      7003397.71      1680490.49      7003497.54
      1680546.91      7003686.34      1680685.15      7003984.42
#Sta/Elev= 30
  4222.0 1648.87  4312.2 1646.22  4390.3 1644.45  4417.4 1642.68  4448.1 1642.76
  4475.2 1641.14  4503.4 1641.03  4610.6 1637.88  4769.4 1637.15  4901.9 1636.47
  4910.4 1636.43  4915.4 1634.83  4928.5 1631.72  4938.7 1630.44  4985.4 1629.50
  4985.9 1629.00  4994.4 1629.50  5008.7 1631.32  5039.8 1632.47  5062.5 1632.40
  5072.9 1631.14  5101.2 1632.31  5111.2 1631.86  5182.7 1633.86  5263.7 1639.17
  5305.9 1641.86  5357.2 1646.58  5448.9 1656.45  5500.2 1663.36  5535.5 1664.56
#Mann=11,-1,0
  4222.0    0.07       0  4312.2   0.035       0  4503.4    0.07       0
  4610.6   0.035       0  4769.4    0.07       0  4901.9   0.035       0
  4915.4    0.07       0  4985.4    0.07       0  4994.4    0.07       0
  5101.2   0.035       0  5263.7    0.07       0
Bank Sta=4985.4,4994.4
Exp/Cntr=0.3,0.1

Type RM Length L Ch R = 1,4444,351,351,351
BEGIN DESCRIPTION:
Mapping XS 64dbc3c8
END DESCRIPTION:
XS GIS Cut Line= 3
      1680721.57      7002673.10      1680153.83      7003084.58
      1679990.64      7003391.86
#Sta/Elev= 30
  4303.4 1649.15  4404.8 1644.61  4493.0 1641.97  4591.2 1638.87  4783.7 1635.29
  4854.9 1630.61  4899.5 1630.11  4918.2 1629.89  4955.3 1629.22  4963.9 1627.27
  4973.7 1623.13  4974.2 1622.63  4983.1 1623.13  5003.2 1626.44  5051.7 1629.15
  5079.4 1632.38  5133.0 1636.48  5139.5 1637.77  5205.6 1645.48  5212.3 1647.27
  5249.6 1651.63  5265.9 1655.42  5271.6 1655.31  5287.9 1658.36  5293.5 1658.01
  5302.8 1659.16  5309.9 1660.87  5315.5 1660.02  5331.8 1661.68  5352.5 1661.77
#Mann=7,-1,0
  4303.4    0.07       0  4493.0   0.035       0  4899.5    0.07       0
  4918.2   0.035       0  4973.7   0.035       0  4983.1   0.035       0
  5139.5    0.07       0
Bank Sta=4973.7,4983.1
Exp/Cntr=0.3,0.1

Type RM Length L Ch R = 1,4093,381,381,381
BEGIN DESCRIPTION:
Mapping XS cb061576
END DESCRIPTION:
XS GIS Cut Line= 3
      1680496.75      7002347.13      1679996.71      7002786.40
      1679611.31      7003091.94
#Sta/Elev= 30
  4336.9 1660.38  4360.1 1659.46  4366.7 1657.89  4374.3 1657.88  4381.0 1655.97
  4388.5 1655.71  4409.4 1651.91  4445.5 1648.06  4565.5 1638.81  4692.5 1633.91
  4820.3 1630.58  4882.2 1627.47  4926.6 1625.28  4940.8 1626.53  4955.0 1626.32
  4962.7 1625.12  4976.8 1623.12  4997.7 1624.36  5013.7 1623.10  5014.2 1622.60
  5023.2 1623.10  5040.9 1626.93  5079.1 1628.85  5225.2 1635.98  5282.9 1641.59
  5345.7 1644.96  5389.3 1648.51  5452.7 1651.22  5475.2 1654.54  5494.3 1655.64
#Mann=9,-1,0
  4336.9    0.07       0  4692.5   0.035       0  4882.2    0.07       0
  4962.7   0.035       0  5013.7   0.035       0  5023.2   0.035       0
  5079.1    0.07       0  5345.7   0.035       0  5389.3    0.07       0
Bank Sta=5013.7,5023.2
Exp/Cntr=0.3,0.1

Type RM Length L Ch R = 1,3712,355,355,355
BEGIN DESCRIPTION:
Mapping XS 85e0dbc8
END DESCRIPTION:
XS GIS Cut Line= 3
      1680264.06      7002040.75      1679791.85      7002479.98
      1679380.42      7002936.54
#Sta/Elev= 30
  4357.7 1677.26  4411.5 1668.46  4425.6 1665.12  4439.8 1663.73  4496.5 1653.16
  4524.8 1648.64  4588.6 1640.38  4673.3 1633.22  4818.2 1628.40  4828.6 1628.10
  4900.1 1625.35  4956.7 1624.59  4987.0 1620.37  4987.5 1619.87  4996.8 1620.37
  5069.5 1626.51  5183.1 1631.28  5218.3 1632.06  5282.5 1635.27  5324.4 1637.65
  5360.3 1641.35  5390.9 1642.81  5423.8 1644.53  5438.0 1646.77  5480.6 1649.26
  5509.0 1650.31  5558.3 1650.66  5572.5 1652.36  5593.5 1653.05  5617.2 1655.48
#Mann=6,-1,0
  4357.7    0.07       0  4818.2   0.035       0  4828.6    0.07       0
  4987.0    0.07       0  4996.8    0.07       0  5390.9   0.035       0
Bank Sta=4987,4996.8
Exp/Cntr=0.3,0.1

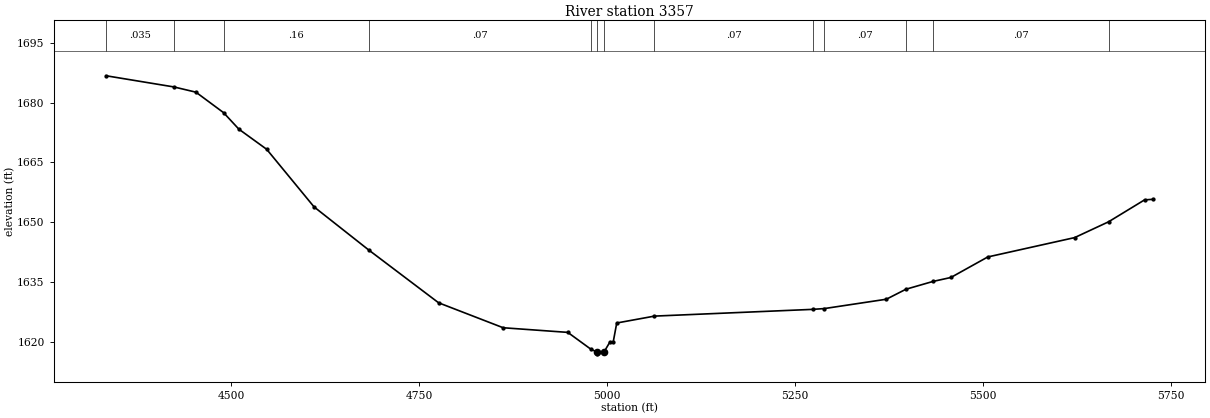
Type RM Length L Ch R = 1,3357,407,407,407
BEGIN DESCRIPTION:
Mapping XS ab3a67de
END DESCRIPTION:
XS GIS Cut Line= 3
      1680198.11      7001794.21      1679651.23      7002188.31
      1679065.79      7002604.00
#Sta/Elev= 30
  4334.0 1686.71  4424.1 1683.91  4453.3 1682.60  4490.1 1677.46  4510.4 1673.33
  4547.4 1668.28  4610.4 1653.84  4683.0 1643.05  4776.0 1629.80  4861.9 1623.54
  4947.8 1622.38  4978.6 1618.15  4986.2 1617.50  4986.7 1617.00  4996.1 1617.50
  5003.5 1619.86  5008.1 1619.86  5012.9 1624.73  5063.1 1626.46  5273.5 1628.15
  5289.0 1628.35  5371.4 1630.69  5397.4 1633.19  5433.4 1635.15  5457.2 1636.14
  5506.3 1641.29  5621.8 1646.14  5666.9 1650.10  5714.8 1655.60  5726.1 1655.74
#Mann=13,-1,0
  4334.0   0.035       0  4424.1    0.07       0  4490.1    0.16       0
  4683.0    0.07       0  4978.6   0.035       0  4986.2   0.035       0
  4996.1   0.035       0  5063.1    0.07       0  5273.5   0.035       0
  5289.0    0.07       0  5397.4   0.035       0  5433.4    0.07       0
  5666.9   0.035       0
Bank Sta=4986.2,4996.1
Exp/Cntr=0.3,0.1