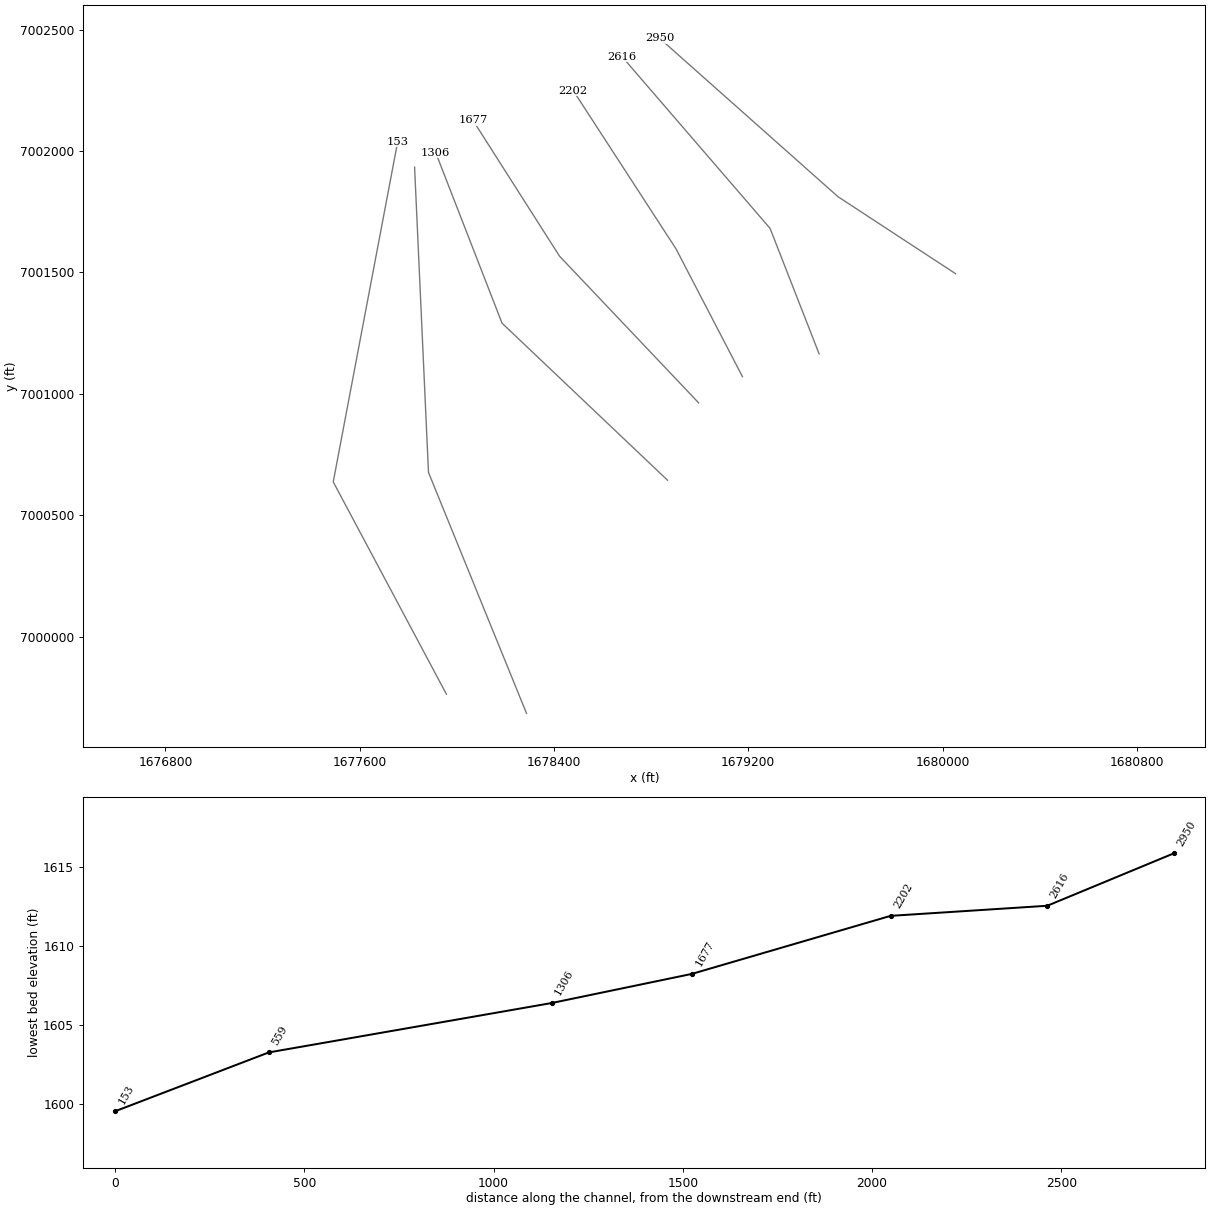
HEC-RAS study Chimney Creek 1169.prj: Chimney Creek 1169 Base Level Engineering

--- Chimney Creek 1169.g01 (geometry) --- (continued)

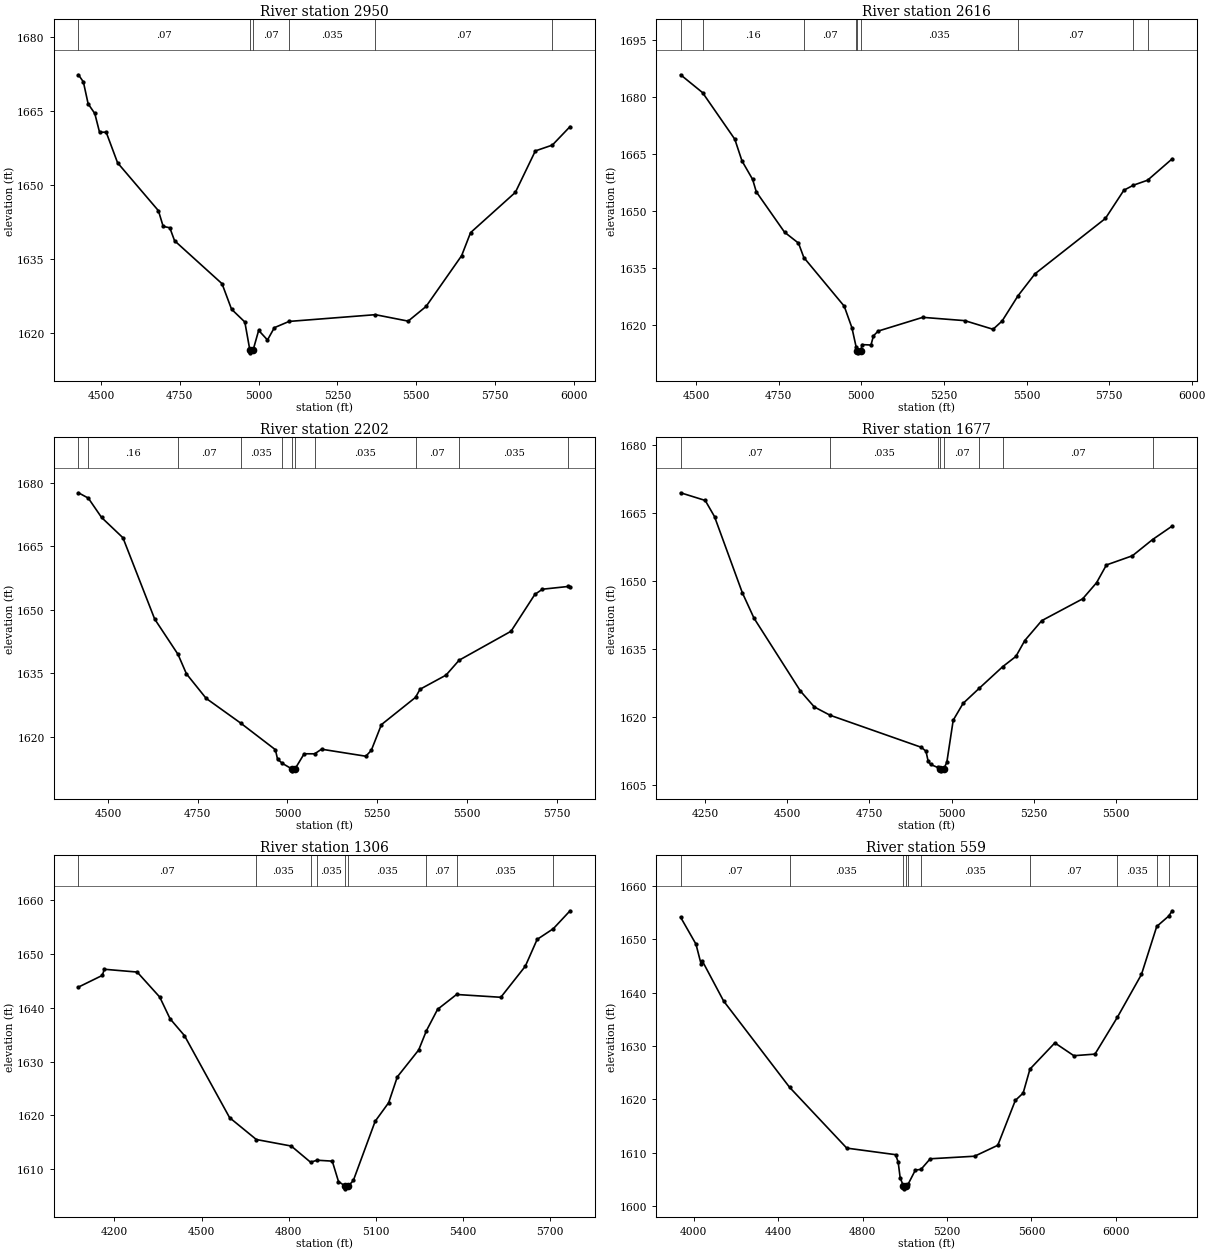
Type RM Length L Ch R = 1,2950,334,334,334
BEGIN DESCRIPTION:
Mapping XS 285923e8
END DESCRIPTION:
XS GIS Cut Line= 3
      1680053.72      7001494.77      1679569.74      7001811.63
      1678835.12      7002463.91
#Sta/Elev= 30
  4428.0 1672.34  4443.7 1670.89  4458.8 1666.44  4479.9 1664.48  4495.0 1660.68
  4516.1 1660.68  4552.3 1654.46  4681.9 1644.74  4697.0 1641.55  4718.1 1641.27
  4733.2 1638.64  4883.9 1629.91  4914.1 1624.73  4956.3 1622.13  4972.4 1616.37
  4972.9 1615.87  4982.3 1616.37  5000.2 1620.43  5028.2 1618.48  5050.0 1620.98
  5096.8 1622.25  5370.7 1623.62  5474.8 1622.31  5531.7 1625.29  5644.6 1635.60
  5673.0 1640.28  5815.2 1648.46  5878.7 1656.88  5932.6 1658.06  5988.9 1661.82
#Mann=6,-1,0
  4428.0    0.07       0  4972.4    0.07       0  4982.3    0.07       0
  5096.8   0.035       0  5370.7    0.07       0  5932.6   0.035       0
Bank Sta=4972.4,4982.3
Exp/Cntr=0.3,0.1

Type RM Length L Ch R = 1,2616,414,414,414
BEGIN DESCRIPTION:
Mapping XS fea40ee0
END DESCRIPTION:
XS GIS Cut Line= 3
      1679491.62      7001164.92      1679289.80      7001681.42
      1678680.02      7002388.85
#Sta/Elev= 30
  4452.7 1685.87  4519.1 1681.17  4616.8 1668.88  4638.5 1663.16  4670.7 1658.29
  4681.9 1655.00  4767.4 1644.36  4809.6 1641.48  4825.8 1637.68  4948.1 1624.85
  4971.4 1619.16  4984.0 1614.15  4987.8 1613.05  4988.3 1612.55  4997.9 1613.05
  5002.4 1614.72  5029.1 1614.61  5036.6 1617.04  5050.9 1618.29  5185.8 1621.91
  5313.1 1621.04  5398.7 1618.76  5426.1 1620.94  5474.3 1627.60  5525.9 1633.41
  5738.8 1647.98  5794.8 1655.43  5823.5 1656.75  5866.6 1658.07  5941.2 1663.72
#Mann=9,-1,0
  4452.7    0.07       0  4519.1    0.16       0  4825.8    0.07       0
  4984.0   0.035       0  4987.8   0.035       0  4997.9   0.035       0
  5474.3    0.07       0  5823.5   0.035       0  5866.6    0.07       0
Bank Sta=4987.8,4997.9
Exp/Cntr=0.3,0.1

Type RM Length L Ch R = 1,2202,525,525,525
BEGIN DESCRIPTION:
Mapping XS bb775e5a
END DESCRIPTION:
XS GIS Cut Line= 3
      1679176.13      7001070.80      1678902.68      7001596.86
      1678479.11      7002249.11
#Sta/Elev= 30
  4417.2 1677.59  4444.7 1676.33  4481.7 1671.76  4541.3 1666.96  4629.7 1647.77
  4694.8 1639.42  4718.3 1634.82  4773.2 1629.03  4869.3 1623.20  4966.3 1616.90
  4972.2 1614.69  4985.7 1613.67  5011.2 1612.41  5011.7 1611.91  5021.3 1612.41
  5046.5 1615.94  5075.7 1615.93  5094.9 1617.02  5218.5 1615.36  5233.7 1616.76
  5261.8 1622.82  5356.9 1629.26  5369.5 1631.18  5442.0 1634.52  5478.5 1638.04
  5623.2 1644.88  5689.7 1653.59  5710.8 1654.81  5782.6 1655.46  5787.8 1655.39
#Mann=11,-1,0
  4417.2    0.07       0  4444.7    0.16       0  4694.8    0.07       0
  4869.3   0.035       0  4985.7    0.07       0  5011.2    0.07       0
  5021.3    0.07       0  5075.7   0.035       0  5356.9    0.07       0
  5478.5   0.035       0  5782.6    0.07       0
Bank Sta=5011.2,5021.3
Exp/Cntr=0.3,0.1

Type RM Length L Ch R = 1,1677,371,371,371
BEGIN DESCRIPTION:
Mapping XS a669fd9c
END DESCRIPTION:
XS GIS Cut Line= 3
      1678995.67      7000962.98      1678422.73      7001567.17
      1678065.99      7002127.03
#Sta/Elev= 30
  4175.1 1669.55  4250.0 1667.86  4278.3 1664.30  4362.9 1647.52  4398.5 1641.90
  4540.0 1625.81  4582.1 1622.32  4630.1 1620.49  4907.8 1613.42  4921.9 1612.57
  4928.8 1610.30  4936.1 1609.64  4957.8 1608.97  4966.2 1608.73  4966.7 1608.23
  4976.4 1608.73  4985.4 1610.09  5004.9 1619.40  5034.9 1623.10  5084.3 1626.45
  5155.7 1631.21  5195.7 1633.46  5222.8 1636.97  5274.4 1641.35  5398.9 1646.16
  5441.2 1649.71  5471.2 1653.63  5550.4 1655.66  5611.8 1659.24  5671.6 1662.22
#Mann=8,-1,0
  4175.1    0.07       0  4630.1   0.035       0  4957.8    0.07       0
  4966.2    0.07       0  4976.4    0.07       0  5084.3   0.035       0
  5155.7    0.07       0  5611.8   0.035       0
Bank Sta=4966.2,4976.4
Exp/Cntr=0.3,0.1

Type RM Length L Ch R = 1,1306,747,747,747
BEGIN DESCRIPTION:
Mapping XS 8d169c46
END DESCRIPTION:
XS GIS Cut Line= 3
      1678867.55      7000644.46      1678186.11      7001291.17
      1677912.92      7001993.66
#Sta/Elev= 30
  4076.1 1643.81  4158.3 1645.98  4165.2 1647.12  4278.4 1646.60  4356.1 1641.96
  4391.7 1637.93  4441.1 1634.82  4596.8 1619.58  4688.8 1615.53  4809.1 1614.32
  4875.5 1611.32  4898.1 1611.69  4950.3 1611.52  4971.7 1607.74  4995.0 1606.88
  4995.5 1606.38  5005.2 1606.88  5022.9 1607.93  5098.0 1618.91  5144.5 1622.36
  5174.4 1627.16  5248.0 1632.15  5274.5 1635.71  5313.1 1639.69  5378.4 1642.44
  5530.8 1641.92  5615.1 1647.68  5655.9 1652.66  5711.5 1654.64  5769.3 1657.97
#Mann=9,-1,0
  4076.1    0.07       0  4688.8   0.035       0  4875.5    0.07       0
  4898.1   0.035       0  4995.0   0.035       0  5005.2   0.035       0
  5274.5    0.07       0  5378.4   0.035       0  5711.5    0.07       0
Bank Sta=4995,5005.2
Exp/Cntr=0.3,0.1

Type RM Length L Ch R = 1,559,406,406,406
BEGIN DESCRIPTION:
Mapping XS a3a7db18
END DESCRIPTION:
XS GIS Cut Line= 3
      1678286.97      6999684.39      1677883.34      7000676.54
      1677826.07      7001933.72
#Sta/Elev= 30
  3937.3 1654.13  4010.1 1649.09  4034.2 1645.38  4039.6 1645.98  4141.2 1638.43
  4453.5 1622.28  4724.6 1610.88  4956.0 1609.65  4968.2 1608.27  4977.6 1605.35
  4993.2 1603.75  4993.7 1603.25  5005.2 1603.75  5016.3 1604.20  5049.9 1606.78
  5075.9 1606.88  5120.0 1608.88  5330.2 1609.36  5440.3 1611.41  5523.3 1619.81
  5560.4 1621.19  5592.7 1625.68  5710.6 1630.59  5800.7 1628.19  5900.8 1628.49
  6007.5 1635.43  6121.0 1643.41  6193.4 1652.40  6249.9 1654.34  6266.9 1655.34
#Mann=10,-1,0
  3937.3    0.07       0  4453.5   0.035       0  4993.2   0.035       0
  5005.2   0.035       0  5016.3    0.07       0  5075.9   0.035       0
  5592.7    0.07       0  6007.5   0.035       0  6193.4    0.07       0
  6249.9   0.035       0
Bank Sta=4993.2,5005.2
Exp/Cntr=0.3,0.1

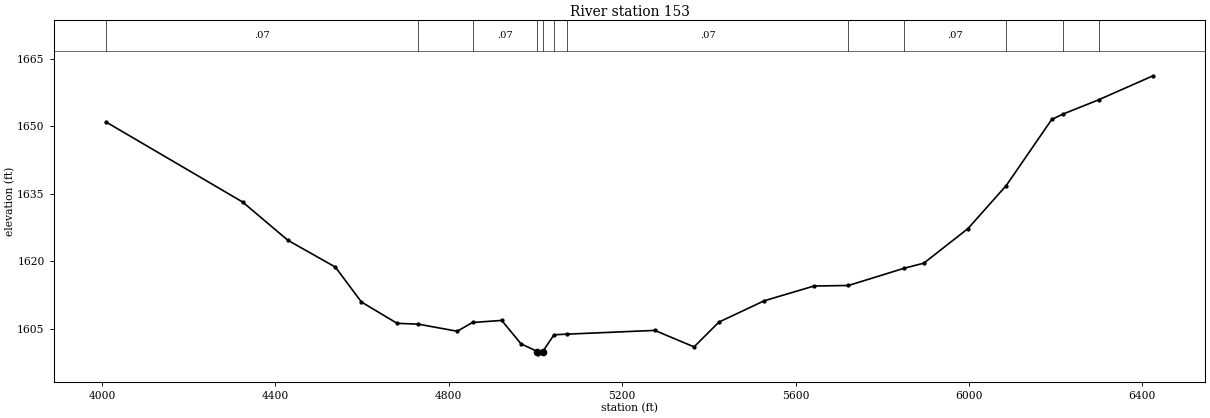
Type RM Length L Ch R = 1,153,0,0,0
BEGIN DESCRIPTION:
Chimney Creek 1169 1.0
END DESCRIPTION:
XS GIS Cut Line= 3
      1677957.17      6999763.37      1677491.12      7000637.49
      1677756.42      7002037.68
#Sta/Elev= 30
  4009.4 1650.91  4324.3 1633.18  4428.4 1624.72  4538.2 1618.76  4598.4 1611.01
  4680.6 1606.29  4729.9 1606.10  4819.3 1604.53  4854.7 1606.47  4922.1 1606.93
  4966.6 1601.74  5004.6 1600.02  5005.1 1599.52  5016.7 1600.02  5042.8 1603.75
  5071.7 1603.88  5275.3 1604.72  5365.9 1601.06  5423.3 1606.56  5527.9 1611.29
  5642.7 1614.56  5722.2 1614.68  5850.8 1618.50  5896.2 1619.63  5998.0 1627.30
  6086.3 1636.84  6191.3 1651.50  6217.3 1652.69  6299.5 1655.85  6425.1 1661.18
#Mann=12,-1,0
  4009.4    0.07       0  4729.9   0.035       0  4854.7    0.07       0
  5004.6    0.07       0  5016.7    0.07       0  5042.8   0.035       0
  5071.7    0.07       0  5722.2   0.035       0  5850.8    0.07       0
  6086.3   0.035       0  6217.3    0.07       0  6299.5   0.035       0
Bank Sta=5004.6,5016.7
Exp/Cntr=0.3,0.1

Chan Stop Cuts=-1