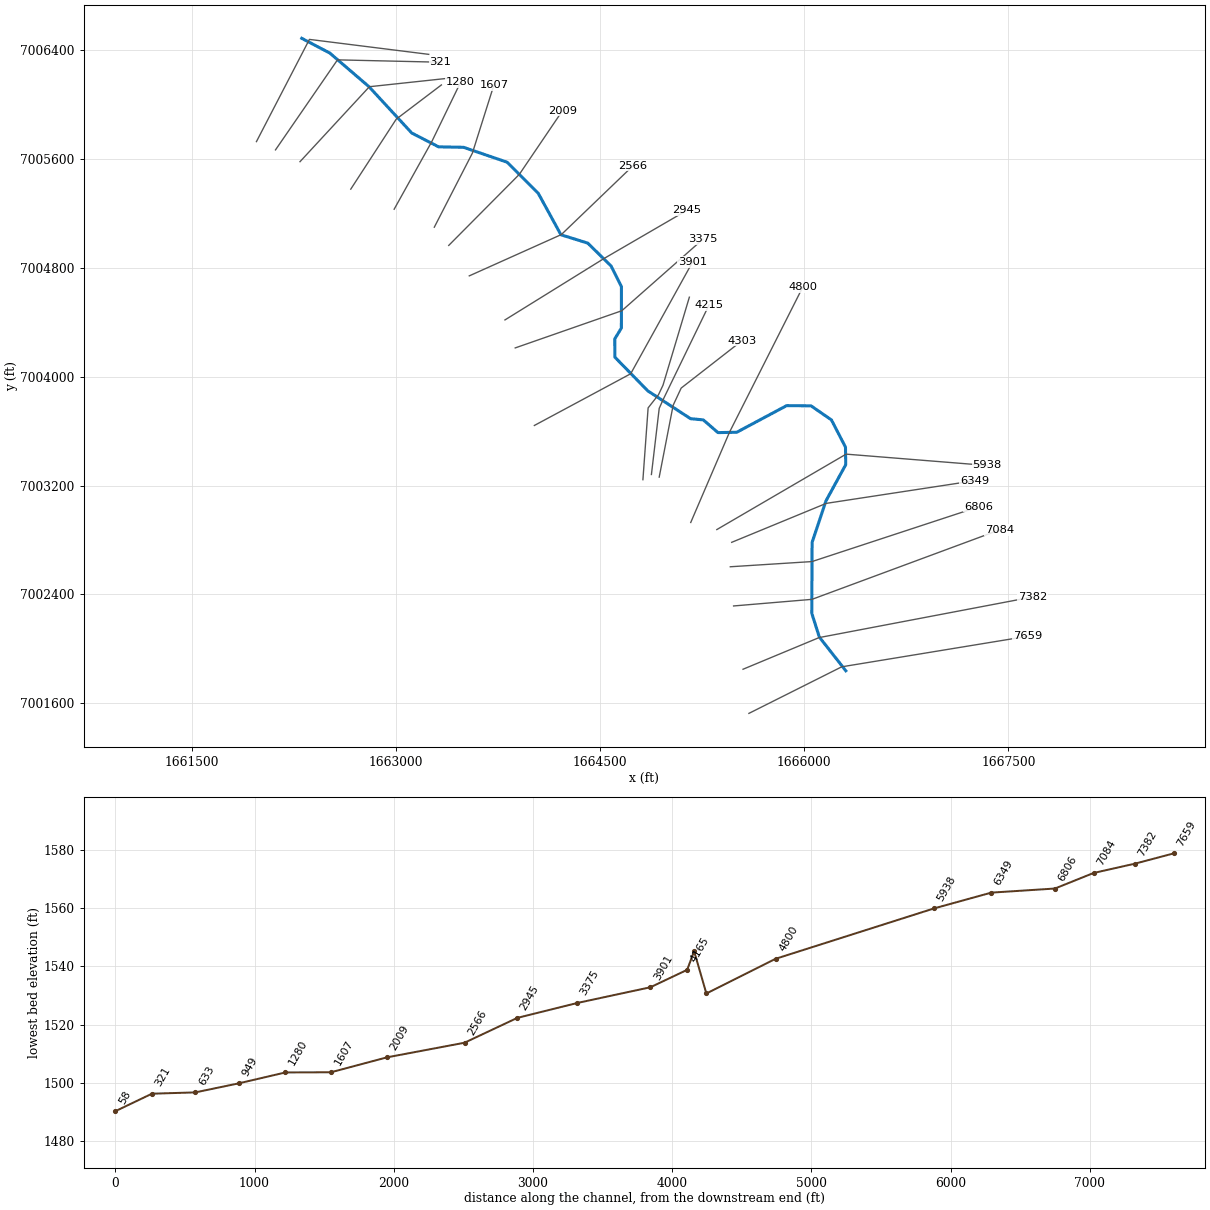
--- Chimney Creek 1171.prj (project) ---

Proj Title=Chimney Creek 1171 Base Level Engineering
Current Plan=p01
Default Exp/Contr=0.3,0.1
English Units
Geom File=g01
Flow File=f01
Plan File=p01
BEGIN DESCRIPTION:
Chimney Creek 1171
END DESCRIPTION:

--- Chimney Creek 1171.p01 (plan) ---

Plan Title=Multiple Run
Short Identifier=Multiple
Geom File=g01
Flow File=f01
Subcritical Flow
K Sum by GR= 0
Std Step Tol= 0.01
Critical Tol= 0.01
Num of Std Step Trials= 20
Max Error Tol= 0.3
Flow Tol Ratio= 0.001
Split Flow NTrial= 30
Split Flow Tol= 0.02
Split Flow Ratio= 0.02
Log Output Level= 0
Friction Slope Method= 1
Unsteady Friction Slope Method= 2
Unsteady Bridges Friction Slope Method= 1
Parabolic Critical Depth
Global Vel Dist=  1 , 1 , 1
Global Log Level= 0
CheckData=True
Encroach Param= -1, 0, 0, 0
BEGIN DESCRIPTION:
Multiple Run
END DESCRIPTION:

--- Chimney Creek 1171.f01 (steady flow) ---

Flow Title=Multiple
Number of Profiles=7
Profile Names=10-year,25-year,50-year,1pct_min,100-year,1pct_plu,500-year
River Rch & RM= Chimney Creek 11,Reach-1,7659
     332     471     590     369     735    1467    1156
River Rch & RM= Chimney Creek 11,Reach-1,6349
     474     688     874     553    1103    2201    1781
Boundary for River Rch & Prof#=Chimney Creek 11,Reach-1,1
Up Type=0
Dn Type=3
Dn Slope=0.005
Boundary for River Rch & Prof#=Chimney Creek 11,Reach-1,2
Up Type=0
Dn Type=3
Dn Slope=0.005
Boundary for River Rch & Prof#=Chimney Creek 11,Reach-1,3
Up Type=0
Dn Type=3
Dn Slope=0.005
Boundary for River Rch & Prof#=Chimney Creek 11,Reach-1,4
Up Type=0
Dn Type=3
Dn Slope=0.005
Boundary for River Rch & Prof#=Chimney Creek 11,Reach-1,5
Up Type=0
Dn Type=3
Dn Slope=0.005
Boundary for River Rch & Prof#=Chimney Creek 11,Reach-1,6
Up Type=0
Dn Type=3
Dn Slope=0.005
Boundary for River Rch & Prof#=Chimney Creek 11,Reach-1,7
Up Type=0
Dn Type=3
Dn Slope=0.005

--- Chimney Creek 1171.g01 (geometry) ---

Geom Title=Existing Conditions

River Reach=Chimney Creek 11,Reach-1
Reach XY= 30
      1666305.00      7001838.00      1666110.52      7002085.57
      1666054.90      7002260.69      1666057.26      7002782.06
      1666158.83      7003086.42      1666304.51      7003353.22
      1666302.77      7003482.07      1666199.41      7003682.39
      1666049.15      7003785.94      1665870.21      7003787.49
      1665503.44      7003591.74      1665365.44      7003589.04
      1665257.36      7003682.44      1665163.48      7003691.50
      1664848.95      7003896.16      1664607.05      7004143.86
      1664606.21      7004277.49      1664654.93      7004358.03
      1664655.21      7004663.09      1664578.71      7004814.82
      1664407.43      7004982.48      1664210.61      7005043.59
      1664044.24      7005347.68      1663814.68      7005577.24
      1663494.49      7005686.78      1663310.93      7005690.24
      1663113.62      7005791.84      1662799.38      7006132.38
      1662511.05      7006379.84      1662305.00      7006488.00

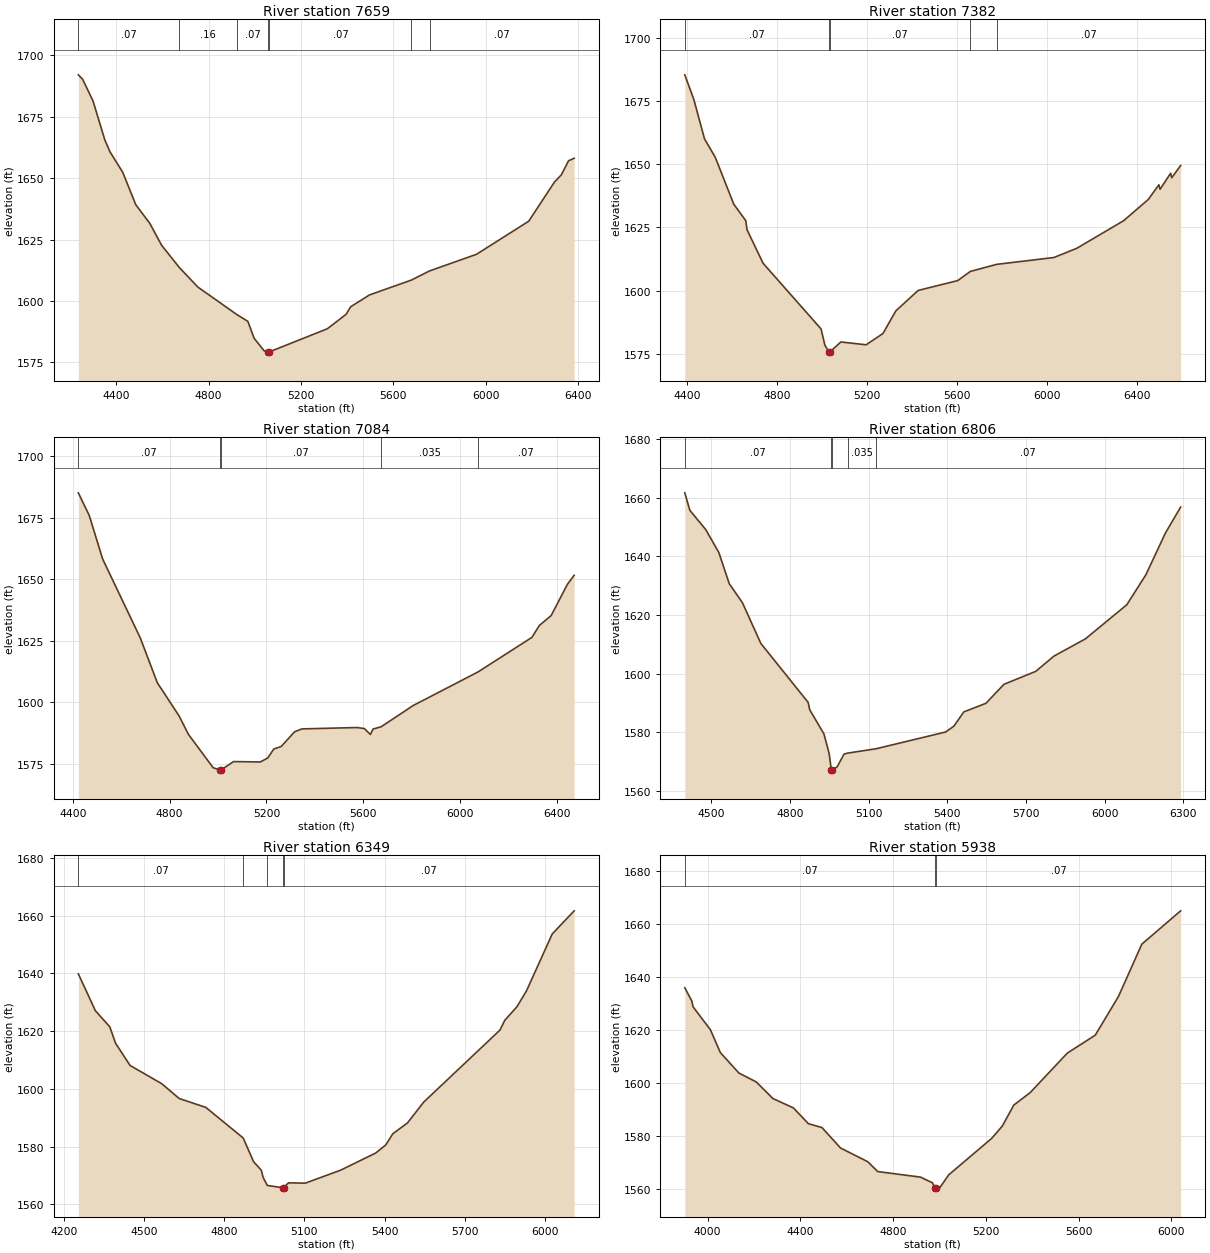
Type RM Length L Ch R = 1,7659,277,277,277
BEGIN DESCRIPTION:
Chimney Creek 1171 16.0
END DESCRIPTION:
XS GIS Cut Line= 3
      1665592.70      7001524.75      1666275.15      7001867.09
      1667639.17      7002091.16
#Sta/Elev= 30
  4236.5 1692.03  4255.4 1690.18  4300.1 1681.40  4350.9 1665.63  4373.3 1660.72
  4428.5 1652.40  4485.2 1639.16  4545.8 1631.60  4597.1 1622.65  4673.5 1613.64
  4753.7 1605.67  4923.3 1594.42  4970.2 1591.72  4997.1 1584.84  5041.0 1579.71
  5058.7 1579.28  5058.9 1578.78  5062.7 1579.28  5314.0 1588.68  5395.1 1594.56
  5415.3 1597.66  5496.4 1602.45  5678.3 1608.52  5756.5 1612.23  5959.7 1619.00
  6185.5 1632.44  6297.0 1648.38  6327.2 1651.37  6357.8 1657.04  6382.3 1658.09
#Mann=7,-1,0
  4236.5    0.07       0  4673.5    0.16       0  4923.3    0.07       0
  5058.7    0.07       0  5062.7    0.07       0  5678.3   0.035       0
  5756.5    0.07       0
Bank Sta=5058.7,5062.7
Exp/Cntr=0.3,0.1

Type RM Length L Ch R = 1,7382,298,298,298
BEGIN DESCRIPTION:
Mapping XS dcba9d99
END DESCRIPTION:
XS GIS Cut Line= 3
      1665549.40      7001849.24      1666108.47      7002081.90
      1667677.87      7002380.50
#Sta/Elev= 30
  4390.5 1685.28  4430.4 1675.63  4478.1 1659.98  4525.8 1652.70  4608.1 1634.15
  4661.2 1627.66  4667.3 1624.00  4738.2 1610.81  4996.0 1584.83  5012.9 1578.42
  5031.2 1575.77  5031.5 1575.27  5035.2 1575.77  5084.1 1579.68  5196.1 1578.57
  5270.9 1583.01  5328.4 1591.99  5427.5 1600.05  5603.3 1603.94  5659.3 1607.56
  5776.2 1610.36  6030.8 1613.07  6132.6 1616.72  6340.4 1627.62  6449.9 1636.01
  6497.0 1641.81  6502.1 1640.03  6549.2 1646.37  6554.3 1644.61  6593.6 1649.42
#Mann=5,-1,0
  4390.5    0.07       0  5031.2    0.07       0  5035.2    0.07       0
  5659.3   0.035       0  5776.2    0.07       0
Bank Sta=5031.2,5035.2
Exp/Cntr=0.3,0.1

Type RM Length L Ch R = 1,7084,278,278,278
BEGIN DESCRIPTION:
Mapping XS 4a463ca0
END DESCRIPTION:
XS GIS Cut Line= 3
      1665480.02      7002314.54      1666056.39      7002363.15
      1667434.06      7002873.27
#Sta/Elev= 30
  4423.0 1685.16  4468.1 1675.95  4523.5 1658.25  4678.9 1626.18  4749.1 1608.00
  4839.5 1594.42  4877.6 1587.01  4980.0 1573.42  5008.6 1572.56  5008.9 1572.06
  5012.6 1572.56  5063.9 1575.94  5174.8 1575.78  5205.2 1577.41  5230.3 1581.06
  5260.7 1582.08  5316.1 1588.06  5346.5 1589.22  5573.7 1589.78  5604.1 1589.36
  5629.1 1586.95  5639.8 1589.15  5673.8 1590.10  5806.2 1598.75  6072.9 1612.33
  6296.2 1626.42  6326.6 1631.24  6375.5 1635.28  6442.9 1648.02  6470.5 1651.65
#Mann=5,-1,0
  4423.0    0.07       0  5008.6    0.07       0  5012.6    0.07       0
  5673.8   0.035       0  6072.9    0.07       0
Bank Sta=5008.6,5012.6
Exp/Cntr=0.3,0.1

Type RM Length L Ch R = 1,6806,457,457,457
BEGIN DESCRIPTION:
Mapping XS b5c73436
END DESCRIPTION:
XS GIS Cut Line= 3
      1665455.69      7002602.73      1666056.39      7002640.92
      1667280.01      7003043.02
#Sta/Elev= 30
  4399.5 1661.63  4418.8 1655.67  4479.0 1649.13  4529.1 1641.31  4569.1 1630.62
  4619.2 1624.16  4689.4 1610.26  4869.8 1590.15  4875.6 1587.66  4929.9 1579.41
  4949.9 1572.65  4957.9 1567.22  4958.2 1566.72  4961.9 1567.22  4980.0 1568.15
  5006.6 1572.56  5022.1 1572.89  5128.2 1574.34  5393.6 1580.06  5425.4 1582.08
  5463.1 1586.92  5547.3 1589.85  5616.2 1596.34  5736.8 1600.72  5807.0 1605.97
  5926.2 1611.81  6084.1 1623.44  6156.9 1633.67  6231.5 1647.93  6289.4 1656.75
#Mann=5,-1,0
  4399.5    0.07       0  4957.9    0.07       0  4961.9    0.07       0
  5022.1   0.035       0  5128.2    0.07       0
Bank Sta=4957.9,4961.9
Exp/Cntr=0.3,0.1

Type RM Length L Ch R = 1,6349,411,411,411
BEGIN DESCRIPTION:
Mapping XS a8fd52f0
END DESCRIPTION:
XS GIS Cut Line= 3
      1665466.13      7002782.43      1666161.42      7003068.88
      1667251.30      7003235.35
#Sta/Elev= 30
  4254.8 1639.88  4318.5 1627.11  4372.5 1621.51  4394.2 1615.81  4448.3 1608.15
  4566.6 1601.83  4632.1 1596.69  4731.8 1593.61  4871.4 1583.02  4910.3 1574.82
  4939.6 1571.80  4945.8 1569.39  4961.7 1566.59  5018.5 1565.81  5018.8 1565.31
  5022.5 1565.81  5040.8 1567.49  5103.4 1567.37  5235.4 1571.85  5367.4 1577.83
  5404.9 1580.64  5430.8 1584.46  5485.9 1588.24  5546.5 1595.44  5831.8 1620.39
  5850.0 1623.80  5895.3 1628.46  5931.0 1633.97  6027.3 1653.67  6109.3 1661.69
#Mann=5,-1,0
  4254.8    0.07       0  4871.4   0.035       0  4961.7    0.07       0
  5018.5    0.07       0  5022.5    0.07       0
Bank Sta=5018.5,5022.5
Exp/Cntr=0.3,0.1

Type RM Length L Ch R = 1,5938,1138,1138,1138
BEGIN DESCRIPTION:
Mapping XS af9879e1
END DESCRIPTION:
XS GIS Cut Line= 3
      1665356.75      7002876.18      1666307.25      7003430.85
      1667341.91      7003347.67
#Sta/Elev= 30
  3901.6 1635.96  3931.7 1631.00  3937.5 1628.74  4012.0 1620.12  4054.9 1611.49
  4135.2 1603.73  4209.6 1600.40  4281.7 1594.11  4370.0 1590.58  4434.5 1584.63
  4493.2 1583.15  4573.4 1575.42  4690.8 1570.24  4733.8 1566.53  4918.5 1564.42
  4968.6 1562.33  4982.3 1560.39  4982.5 1559.89  4986.4 1560.39  5002.1 1560.51
  5040.0 1565.30  5225.2 1579.06  5270.7 1583.68  5320.9 1591.66  5391.1 1596.34
  5551.6 1611.29  5672.0 1618.06  5772.3 1632.72  5872.7 1652.43  6040.1 1665.03
#Mann=3,-1,0
  3901.6    0.07       0  4982.3    0.07       0  4986.4    0.07       0
Bank Sta=4982.3,4986.4
Exp/Cntr=0.3,0.1

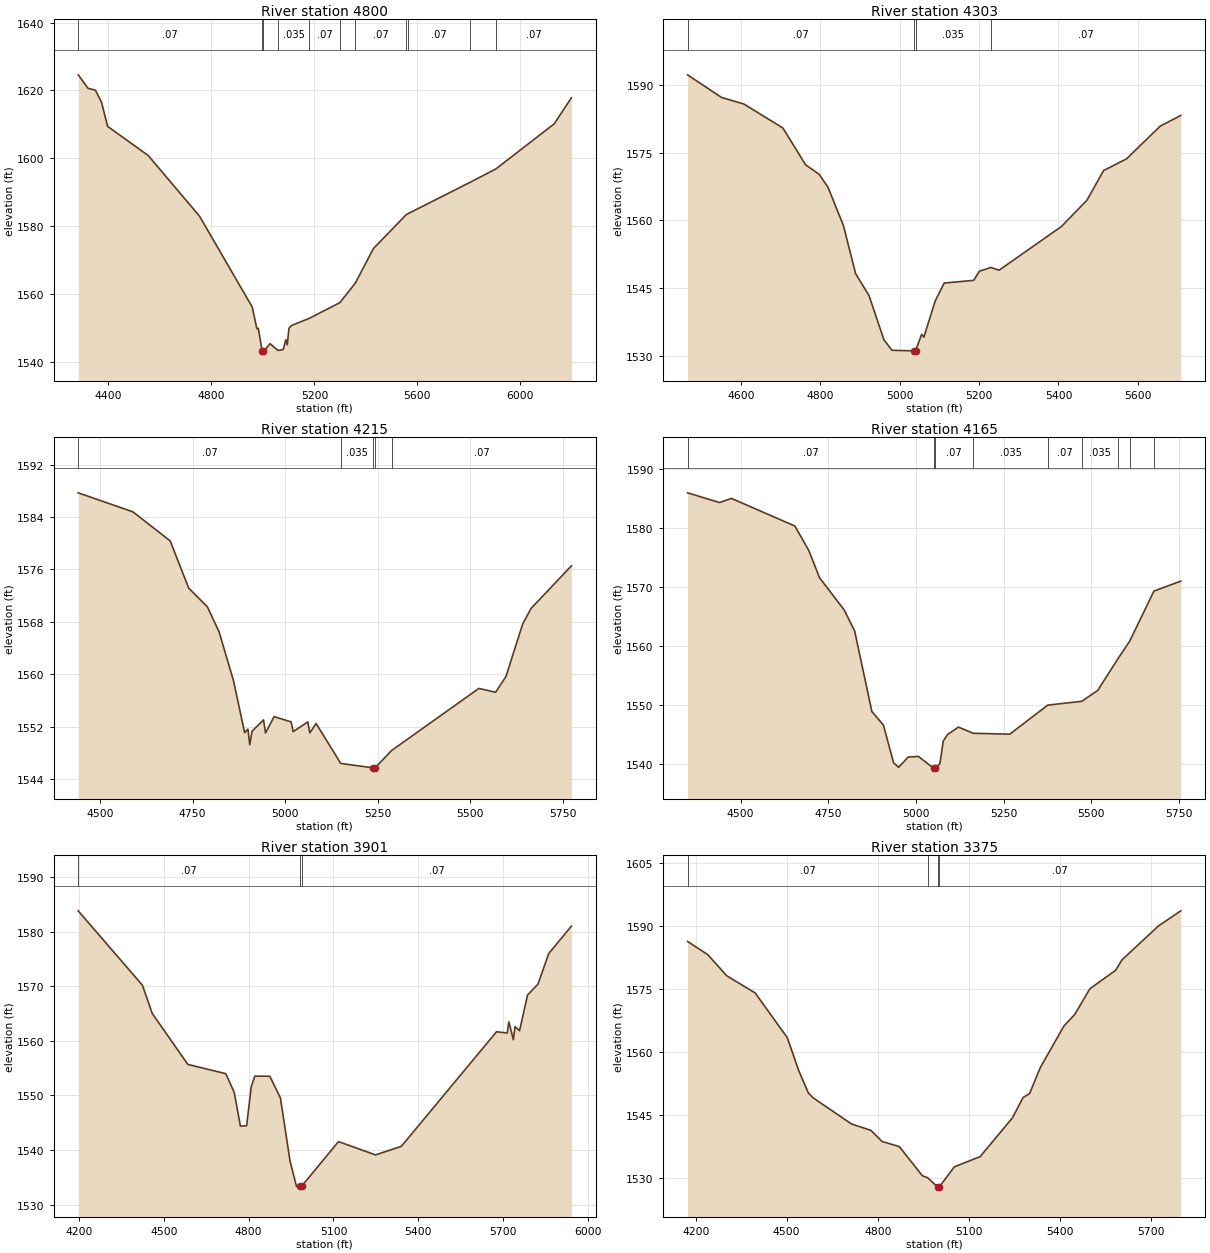
Type RM Length L Ch R = 1,4800,497,497,497
BEGIN DESCRIPTION:
Mapping XS d3913600
END DESCRIPTION:
XS GIS Cut Line= 3
      1665164.89      7002928.23      1665449.62      7003591.44
      1665987.82      7004657.43
#Sta/Elev= 30
  4282.5 1624.60  4320.6 1620.63  4349.6 1620.06  4373.1 1616.52  4396.7 1609.42
  4554.4 1600.83  4753.7 1582.96  4958.5 1556.18  4976.6 1549.78  4982.0 1549.92
  4997.4 1543.09  4997.7 1542.59  5001.9 1543.09  5027.8 1545.38  5058.7 1543.37
  5078.8 1543.65  5089.1 1546.54  5094.7 1545.06  5101.2 1549.94  5111.4 1550.75
  5179.6 1552.82  5298.8 1557.46  5358.9 1563.21  5429.2 1573.40  5556.3 1583.37
  5561.7 1583.61  5802.8 1592.85  5905.3 1596.88  6131.4 1610.16  6198.4 1617.85
#Mann=11,-1,0
  4282.5    0.07       0  4997.4    0.07       0  5001.9    0.07       0
  5058.7   0.035       0  5179.6    0.07       0  5298.8   0.035       0
  5358.9    0.07       0  5556.3   0.035       0  5561.7    0.07       0
  5802.8   0.035       0  5905.3    0.07       0
Bank Sta=4997.4,5001.9
Exp/Cntr=0.3,0.1

Type RM Length L Ch R = 1,4303,88,88,88
BEGIN DESCRIPTION:
Mapping XS 1a4ef012
END DESCRIPTION:
XS GIS Cut Line= 4
      1664933.12      7003261.98      1665035.55      7003789.80
      1665094.58      7003916.53      1665541.25      7004264.52
#Sta/Elev= 30
  4464.7 1592.18  4550.3 1587.19  4607.1 1585.71  4705.1 1580.44  4762.2 1572.33
  4796.8 1570.18  4819.0 1567.32  4857.9 1558.86  4888.5 1548.25  4922.4 1543.39
  4959.8 1533.66  4980.2 1531.31  5035.5 1531.18  5035.8 1530.68  5040.0 1531.18
  5040.6 1531.42  5055.1 1534.83  5060.7 1534.21  5089.1 1542.19  5111.9 1546.17
  5186.2 1546.76  5200.6 1548.78  5229.6 1549.61  5250.4 1549.01  5407.8 1558.68
  5472.0 1564.49  5513.7 1571.02  5571.6 1573.61  5656.6 1580.84  5708.4 1583.20
#Mann=5,-1,0
  4464.7    0.07       0  5035.5    0.07       0  5040.0    0.07       0
  5040.6   0.035       0  5229.6    0.07       0
Bank Sta=5035.5,5040
Exp/Cntr=0.3,0.1

Type RM Length L Ch R = 1,4215,50,50,50
BEGIN DESCRIPTION:
Mapping XS caeb2d2f
END DESCRIPTION:
XS GIS Cut Line= 4
      1664875.83      7003281.11      1664933.12      7003767.23
      1664962.64      7003833.20      1665299.46      7004527.68
#Sta/Elev= 30
  4440.5 1587.68  4588.4 1584.78  4689.1 1580.35  4739.4 1573.12  4789.8 1570.28
  4821.4 1566.45  4860.3 1559.02  4890.5 1551.07  4899.4 1551.61  4904.4 1549.21
  4910.6 1551.29  4941.6 1553.01  4947.0 1551.02  4970.2 1553.51  5016.1 1552.71
  5021.7 1551.22  5061.3 1552.71  5066.8 1551.04  5083.8 1552.46  5150.5 1546.36
  5238.7 1545.69  5239.0 1545.19  5243.2 1545.69  5287.7 1548.33  5523.8 1557.82
  5569.0 1557.23  5597.1 1559.64  5642.2 1567.64  5664.8 1570.02  5774.1 1576.54
#Mann=5,-1,0
  4440.5    0.07       0  5150.5   0.035       0  5238.7    0.07       0
  5243.2   0.035       0  5287.7    0.07       0
Bank Sta=5238.7,5243.2
Exp/Cntr=0.3,0.1

Type RM Length L Ch R = 1,4165,264,264,264
BEGIN DESCRIPTION:
Mapping XS 51953efe
END DESCRIPTION:
XS GIS Cut Line= 5
      1664813.33      7003242.90      1664851.53      7003770.70
      1664927.91      7003867.92      1664960.90      7003937.36
      1665154.80      7004584.86
#Sta/Elev= 30
  4349.0 1586.01  4440.4 1584.36  4474.4 1585.06  4654.9 1580.38  4695.0 1576.18
  4725.1 1571.62  4795.3 1566.15  4825.3 1562.58  4874.3 1548.92  4907.3 1546.60
  4936.2 1540.23  4950.7 1539.44  4977.8 1541.19  5007.1 1541.29  5050.3 1539.30
  5050.6 1538.80  5054.8 1539.30  5068.3 1540.08  5077.7 1543.89  5089.8 1545.00
  5121.1 1546.27  5163.2 1545.22  5267.3 1545.07  5375.7 1550.00  5472.2 1550.64
  5517.8 1552.48  5575.1 1557.82  5609.2 1560.86  5678.1 1569.34  5754.6 1571.03
#Mann=9,-1,0
  4349.0    0.07       0  5050.3    0.07       0  5054.8    0.07       0
  5163.2   0.035       0  5375.7    0.07       0  5472.2   0.035       0
  5575.1    0.07       0  5609.2   0.035       0  5678.1    0.07       0
Bank Sta=5050.3,5054.8
Exp/Cntr=0.3,0.1

Type RM Length L Ch R = 1,3901,526,526,526
BEGIN DESCRIPTION:
Mapping XS c1f17f5f
END DESCRIPTION:
XS GIS Cut Line= 3
      1664015.11      7003641.53      1664723.43      7004021.73
      1665178.68      7004843.78
#Sta/Elev= 30
  4197.7 1583.81  4424.6 1570.19  4459.4 1565.02  4585.3 1555.67  4719.7 1553.97
  4749.3 1550.53  4771.2 1544.36  4793.1 1544.43  4809.4 1551.58  4821.8 1553.52
  4875.2 1553.50  4912.6 1549.52  4946.6 1537.96  4969.3 1533.34  4982.5 1533.32
  4982.8 1532.82  4987.1 1533.32  5117.9 1541.53  5248.8 1539.09  5340.0 1540.66
  5676.6 1561.66  5714.4 1561.42  5720.1 1563.47  5736.1 1560.19  5741.8 1562.59
  5757.9 1561.84  5786.1 1568.37  5823.1 1570.38  5860.9 1575.97  5941.3 1581.02
#Mann=3,-1,0
  4197.7    0.07       0  4982.5    0.07       0  4987.1    0.07       0
Bank Sta=4982.5,4987.1
Exp/Cntr=0.3,0.1

Type RM Length L Ch R = 1,3375,430,430,430
BEGIN DESCRIPTION:
Mapping XS 2f980914
END DESCRIPTION:
XS GIS Cut Line= 3
      1663874.45      7004211.82      1664658.33      7004485.27
      1665254.68      7005011.31
#Sta/Elev= 30
  4173.3 1586.35  4240.2 1583.18  4302.3 1578.19  4396.3 1574.08  4502.2 1563.43
  4540.2 1555.53  4571.3 1550.33  4586.9 1549.14  4714.0 1542.90  4777.6 1541.39
  4814.5 1538.75  4871.4 1537.52  4947.0 1530.62  4964.6 1530.12  4997.5 1527.91
  4997.9 1527.41  5002.7 1527.91  5052.4 1532.70  5137.6 1535.15  5243.8 1544.34
  5279.1 1549.20  5300.7 1550.16  5335.9 1556.34  5413.7 1566.21  5449.7 1569.00
  5499.0 1575.06  5584.4 1579.49  5605.3 1581.97  5725.7 1590.05  5798.7 1593.62
#Mann=4,-1,0
  4173.3    0.07       0  4964.6   0.035       0  4997.5    0.07       0
  5002.7    0.07       0
Bank Sta=4997.5,5002.7
Exp/Cntr=0.3,0.1

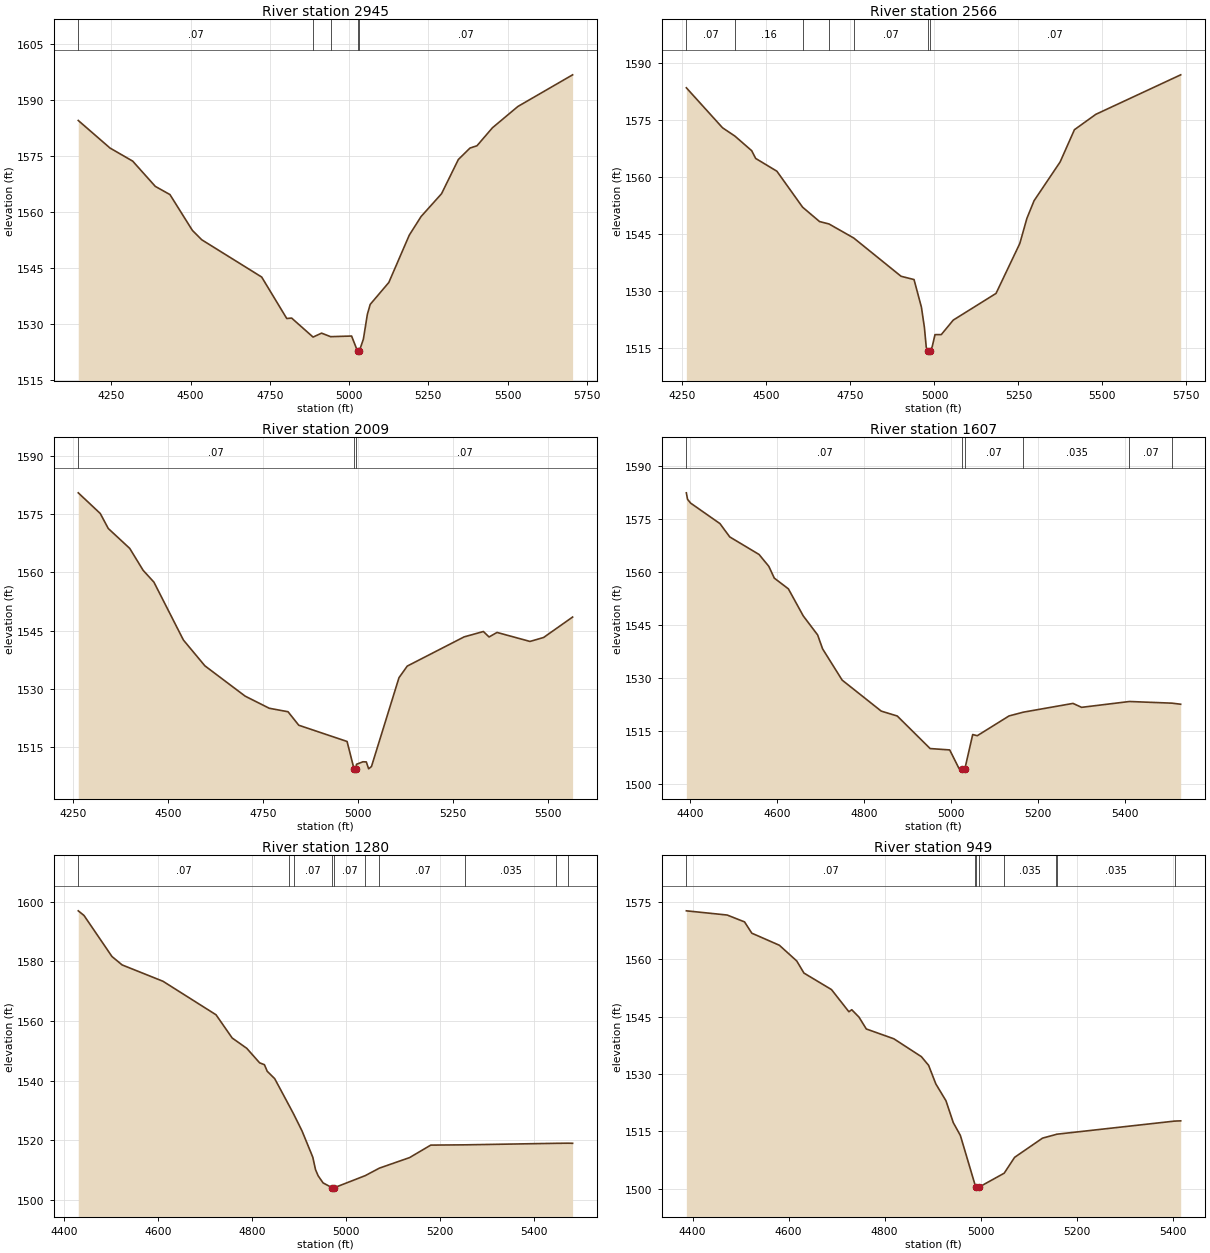
Type RM Length L Ch R = 1,2945,379,379,379
BEGIN DESCRIPTION:
Mapping XS 8b5eb05b
END DESCRIPTION:
XS GIS Cut Line= 3
      1663798.98      7004417.58      1664525.51      7004868.08
      1665134.90      7005222.25
#Sta/Elev= 30
  4145.5 1584.49  4245.7 1577.12  4317.3 1573.62  4388.6 1566.87  4434.8 1564.68
  4505.6 1555.11  4535.1 1552.60  4724.2 1542.64  4803.3 1531.56  4818.7 1531.67
  4886.4 1526.59  4913.2 1527.64  4941.7 1526.70  5007.9 1526.87  5026.7 1522.80
  5027.1 1522.30  5032.0 1522.80  5045.1 1526.04  5057.6 1532.66  5066.6 1535.32
  5125.4 1541.19  5189.9 1553.84  5227.2 1558.82  5291.7 1564.91  5344.7 1574.05
  5381.5 1577.12  5403.5 1577.73  5452.3 1582.54  5532.6 1588.23  5705.2 1596.69
#Mann=5,-1,0
  4145.5    0.07       0  4886.4   0.035       0  4941.7    0.07       0
  5026.7    0.07       0  5032.0    0.07       0
Bank Sta=5026.7,5032
Exp/Cntr=0.3,0.1

Type RM Length L Ch R = 1,2566,557,557,557
BEGIN DESCRIPTION:
Mapping XS e1c2666c
END DESCRIPTION:
XS GIS Cut Line= 3
      1663536.66      7004741.49      1664213.78      7005045.32
      1664739.81      7005550.52
#Sta/Elev= 30
  4261.5 1583.58  4369.3 1573.05  4405.8 1570.89  4456.0 1567.03  4467.9 1564.99
  4531.0 1561.63  4607.5 1552.17  4657.9 1548.39  4686.2 1547.75  4759.7 1544.06
  4900.6 1533.99  4939.2 1533.13  4961.2 1525.87  4970.1 1520.54  4975.6 1515.33
  4980.4 1514.27  4980.8 1513.77  4985.7 1514.27  4993.3 1515.44  5001.6 1518.63
  5020.4 1518.65  5056.0 1522.46  5183.3 1529.48  5254.1 1542.62  5275.2 1549.23
  5296.5 1553.86  5374.2 1564.08  5416.7 1572.55  5480.2 1576.59  5733.0 1586.99
#Mann=7,-1,0
  4261.5    0.07       0  4405.8    0.16       0  4607.5    0.07       0
  4686.2    0.16       0  4759.7    0.07       0  4980.4    0.07       0
  4985.7    0.07       0
Bank Sta=4980.4,4985.7
Exp/Cntr=0.3,0.1

Type RM Length L Ch R = 1,2009,402,402,402
BEGIN DESCRIPTION:
Mapping XS 99525cf2
END DESCRIPTION:
XS GIS Cut Line= 3
      1663385.63      7004965.44      1663904.75      7005488.03
      1664222.47      7005956.80
#Sta/Elev= 30
  4263.2 1580.55  4321.2 1575.22  4342.3 1571.35  4398.9 1566.21  4434.3 1560.54
  4462.6 1557.51  4540.3 1542.58  4596.9 1535.92  4703.0 1528.10  4766.6 1524.97
  4816.1 1524.07  4844.4 1520.59  4971.7 1516.40  4990.2 1509.25  4990.6 1508.75
  4995.6 1509.25  4996.4 1510.51  5013.5 1511.16  5022.4 1511.13  5028.5 1509.35
  5036.0 1509.94  5108.5 1532.85  5130.3 1535.85  5280.1 1543.38  5331.0 1544.77
  5345.9 1543.36  5366.9 1544.53  5453.8 1542.21  5489.7 1543.23  5566.1 1548.50
#Mann=3,-1,0
  4263.2    0.07       0  4990.2    0.07       0  4995.6    0.07       0
Bank Sta=4990.2,4995.6
Exp/Cntr=0.3,0.1

Type RM Length L Ch R = 1,1607,327,327,327
BEGIN DESCRIPTION:
Mapping XS ece5f0de
END DESCRIPTION:
XS GIS Cut Line= 3
      1663279.46      7005099.28      1663559.41      7005643.99
      1663717.47      7006144.17
#Sta/Elev= 30
  4390.6 1582.29  4393.3 1580.47  4400.4 1579.39  4467.9 1573.59  4490.4 1569.83
  4557.8 1564.87  4580.3 1561.51  4592.9 1558.18  4625.3 1555.15  4659.5 1547.50
  4692.6 1542.12  4704.0 1538.18  4749.0 1529.35  4838.9 1520.59  4875.7 1519.21
  4951.3 1510.01  4996.3 1509.62  5017.7 1504.39  5025.5 1504.13  5025.9 1503.63
  5030.9 1504.13  5049.2 1513.97  5059.7 1513.64  5132.8 1519.23  5165.9 1520.30
  5279.9 1522.77  5299.7 1521.66  5409.8 1523.31  5507.6 1522.84  5527.6 1522.54
#Mann=6,-1,0
  4390.6    0.07       0  5025.5    0.07       0  5030.9    0.07       0
  5165.9   0.035       0  5409.8    0.07       0  5507.6   0.035       0
Bank Sta=5025.5,5030.9
Exp/Cntr=0.3,0.1

Type RM Length L Ch R = 1,1280,331,331,331
BEGIN DESCRIPTION:
Mapping XS 82d79ac3
END DESCRIPTION:
XS GIS Cut Line= 3
      1662984.31      7005231.65      1663262.10      7005730.80
      1663472.16      7006163.91
#Sta/Elev= 30
  4430.5 1596.94  4442.8 1595.37  4502.3 1581.61  4524.0 1578.78  4610.9 1573.31
  4723.9 1562.06  4758.2 1554.28  4789.3 1550.81  4816.7 1545.94  4826.9 1545.32
  4832.8 1543.12  4848.8 1540.63  4879.5 1531.61  4889.2 1528.74  4907.0 1523.09
  4929.9 1514.28  4935.7 1510.10  4941.4 1508.02  4951.7 1505.67  4970.6 1504.07
  4971.1 1503.57  4976.1 1504.07  5041.6 1508.10  5071.8 1510.62  5136.0 1514.15
  5181.1 1518.34  5254.8 1518.43  5447.4 1518.94  5473.7 1518.98  5483.1 1518.95
#Mann=10,-1,0
  4430.5    0.07       0  4879.5    0.16       0  4889.2    0.07       0
  4970.6    0.07       0  4976.1    0.07       0  5041.6   0.035       0
  5071.8    0.07       0  5254.8   0.035       0  5447.4    0.07       0
  5473.7   0.035       0
Bank Sta=4970.6,4976.1
Exp/Cntr=0.3,0.1

Type RM Length L Ch R = 1,949,316,316,316
BEGIN DESCRIPTION:
Mapping XS 98ab5bf8
END DESCRIPTION:
XS GIS Cut Line= 3
      1662665.29      7005379.20      1662999.51      7005893.56
      1663331.56      7006145.30
#Sta/Elev= 30
  4386.8 1572.72  4471.8 1571.62  4508.1 1569.82  4523.2 1566.87  4580.6 1563.71
  4616.8 1559.60  4631.9 1556.42  4689.3 1552.10  4725.5 1546.30  4731.5 1546.83
  4746.6 1544.89  4761.8 1541.79  4819.1 1539.23  4876.5 1534.55  4891.6 1532.28
  4906.7 1527.40  4927.8 1523.00  4943.0 1517.28  4957.8 1513.92  4988.4 1500.98
  4990.8 1500.37  4991.3 1499.87  4996.3 1500.37  5049.1 1504.04  5070.8 1508.19
  5129.0 1513.22  5156.3 1514.15  5158.3 1514.24  5404.4 1517.68  5416.9 1517.74
#Mann=8,-1,0
  4386.8    0.07       0  4988.4    0.16       0  4990.8    0.07       0
  4996.3    0.16       0  5049.1   0.035       0  5156.3    0.07       0
  5158.3   0.035       0  5404.4    0.07       0
Bank Sta=4990.8,4996.3
Exp/Cntr=0.3,0.1

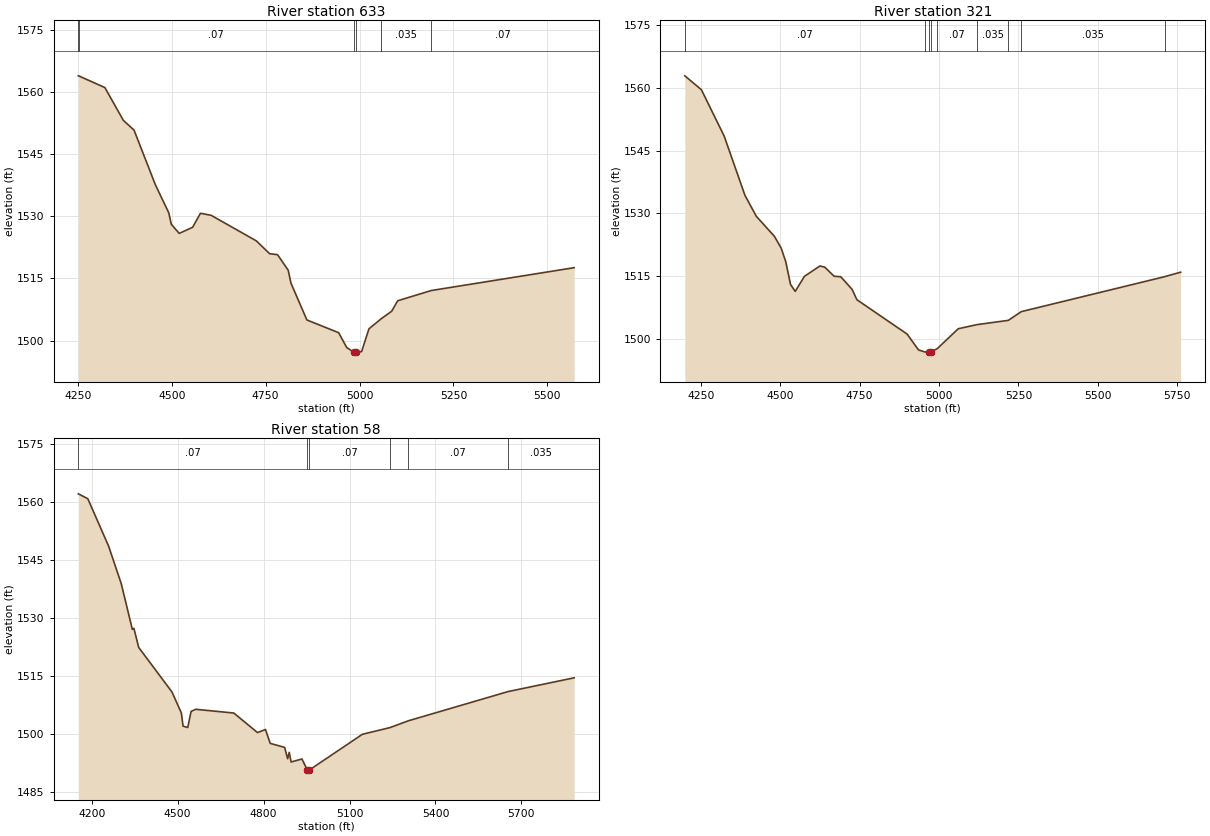
Type RM Length L Ch R = 1,633,312,312,312
BEGIN DESCRIPTION:
Mapping XS 099bc9f4
END DESCRIPTION:
XS GIS Cut Line= 3
      1662292.06      7005581.07      1662802.03      7006132.27
      1663368.25      7006193.02
#Sta/Elev= 30
  4251.2 1563.94  4252.2 1563.93  4321.9 1561.10  4371.2 1553.17  4399.6 1550.82
  4456.3 1537.64  4492.0 1530.87  4498.8 1528.09  4519.8 1525.88  4555.5 1527.35
  4576.5 1530.74  4604.8 1530.25  4725.0 1524.09  4760.7 1520.97  4781.7 1520.74
  4810.1 1516.99  4817.4 1513.88  4859.9 1504.97  4944.4 1501.90  4966.0 1498.30
  4984.2 1497.22  4984.7 1496.72  4989.7 1497.22  5005.5 1497.32  5025.2 1502.84
  5058.2 1505.29  5085.6 1507.08  5101.7 1509.61  5190.9 1512.08  5571.6 1517.60
#Mann=6,-1,0
  4251.2   0.035       0  4252.2    0.07       0  4984.2    0.07       0
  4989.7    0.07       0  5058.2   0.035       0  5190.9    0.07       0
Bank Sta=4984.2,4989.7
Exp/Cntr=0.3,0.1

Type RM Length L Ch R = 1,321,263,263,263
BEGIN DESCRIPTION:
Mapping XS 31ad09cc
END DESCRIPTION:
XS GIS Cut Line= 3
      1662111.92      7005667.85      1662567.66      7006329.75
      1663325.03      7006312.39
#Sta/Elev= 30
  4199.4 1562.94  4251.6 1559.62  4323.3 1548.52  4388.9 1534.29  4424.7 1529.28
  4481.5 1524.50  4503.1 1521.64  4517.4 1518.38  4532.3 1512.96  4547.1 1511.30
  4576.0 1514.90  4624.9 1517.39  4639.8 1517.12  4669.6 1514.93  4690.5 1514.81
  4726.4 1511.76  4741.3 1509.30  4899.5 1501.07  4935.4 1497.26  4955.4 1496.80
  4968.4 1496.77  4968.9 1496.27  4974.0 1496.77  4994.5 1497.60  5060.4 1502.35
  5119.0 1503.33  5218.1 1504.36  5259.0 1506.45  5710.1 1514.82  5760.6 1515.90
#Mann=9,-1,0
  4199.4    0.07       0  4955.4   0.035       0  4968.4    0.07       0
  4974.0   0.035       0  4994.5    0.07       0  5119.0   0.035       0
  5218.1    0.07       0  5259.0   0.035       0  5710.1    0.07       0
Bank Sta=4968.4,4974
Exp/Cntr=0.3,0.1

Type RM Length L Ch R = 1,58,0,0,0
BEGIN DESCRIPTION:
Chimney Creek 1171 1.0
END DESCRIPTION:
XS GIS Cut Line= 3
      1661971.74      7005728.63      1662361.20      7006480.21
      1663238.44      7006370.23
#Sta/Elev= 30
  4153.5 1562.04  4186.6 1560.78  4259.1 1548.56  4303.4 1538.84  4342.0 1527.08
  4347.6 1527.34  4364.1 1522.43  4480.4 1510.92  4513.2 1505.49  4519.0 1502.11
  4535.5 1501.76  4547.0 1505.91  4563.3 1506.46  4696.1 1505.49  4779.0 1500.45
  4806.7 1501.25  4823.2 1497.67  4873.6 1496.63  4884.0 1493.71  4889.6 1495.35
  4896.1 1492.86  4933.9 1493.64  4953.2 1490.75  4953.7 1490.25  4958.8 1490.75
  5144.9 1500.01  5241.4 1501.74  5305.8 1503.50  5653.5 1511.03  5884.1 1514.58
#Mann=6,-1,0
  4153.5    0.07       0  4953.2    0.07       0  4958.8    0.07       0
  5241.4   0.035       0  5305.8    0.07       0  5653.5   0.035       0
Bank Sta=4953.2,4958.8
Exp/Cntr=0.3,0.1

Chan Stop Cuts=-1