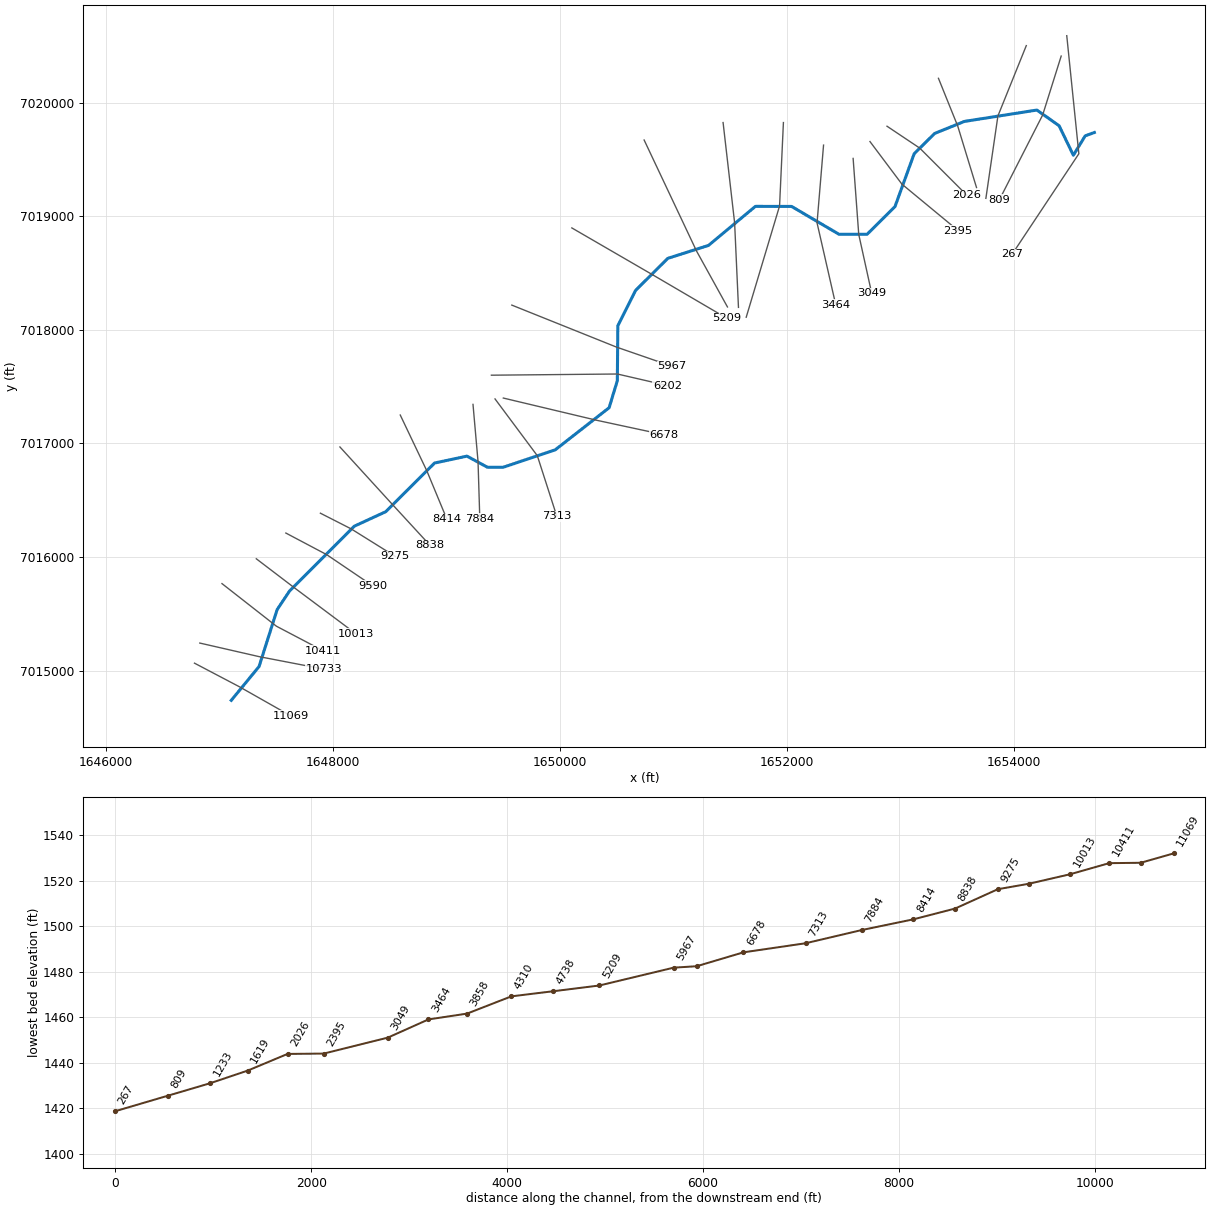
--- Chimney Creek 1172.prj (project) ---

Proj Title=Chimney Creek 1172 Base Level Engineering
Current Plan=p01
Default Exp/Contr=0.3,0.1
English Units
Geom File=g01
Flow File=f01
Plan File=p01
BEGIN DESCRIPTION:
Chimney Creek 1172
END DESCRIPTION:

--- Chimney Creek 1172.p01 (plan) ---

Plan Title=Multiple Run
Short Identifier=Multiple
Geom File=g01
Flow File=f01
Subcritical Flow
K Sum by GR= 0
Std Step Tol= 0.01
Critical Tol= 0.01
Num of Std Step Trials= 20
Max Error Tol= 0.3
Flow Tol Ratio= 0.001
Split Flow NTrial= 30
Split Flow Tol= 0.02
Split Flow Ratio= 0.02
Log Output Level= 0
Friction Slope Method= 1
Unsteady Friction Slope Method= 2
Unsteady Bridges Friction Slope Method= 1
Parabolic Critical Depth
Global Vel Dist=  1 , 1 , 1
Global Log Level= 0
CheckData=True
Encroach Param= -1, 0, 0, 0
BEGIN DESCRIPTION:
Multiple Run
END DESCRIPTION:

--- Chimney Creek 1172.f01 (steady flow) ---

Flow Title=Multiple
Number of Profiles=7
Profile Names=10-year,25-year,50-year,1pct_min,100-year,1pct_plu,500-year
River Rch & RM= Chimney Creek 11,Reach-1,11069
     351     496     619     384     766    1529    1191
River Rch & RM= Chimney Creek 11,Reach-1,8838
     509     735     929     584    1166    2326    1860
River Rch & RM= Chimney Creek 11,Reach-1,5967
     632     921    1172     742    1480    2953    2390
River Rch & RM= Chimney Creek 11,Reach-1,1619
     710    1041    1331     845    1687    3366    2747
Boundary for River Rch & Prof#=Chimney Creek 11,Reach-1,1
Up Type=0
Dn Type=3
Dn Slope=0.005
Boundary for River Rch & Prof#=Chimney Creek 11,Reach-1,2
Up Type=0
Dn Type=3
Dn Slope=0.005
Boundary for River Rch & Prof#=Chimney Creek 11,Reach-1,3
Up Type=0
Dn Type=3
Dn Slope=0.005
Boundary for River Rch & Prof#=Chimney Creek 11,Reach-1,4
Up Type=0
Dn Type=3
Dn Slope=0.005
Boundary for River Rch & Prof#=Chimney Creek 11,Reach-1,5
Up Type=0
Dn Type=3
Dn Slope=0.005
Boundary for River Rch & Prof#=Chimney Creek 11,Reach-1,6
Up Type=0
Dn Type=3
Dn Slope=0.005
Boundary for River Rch & Prof#=Chimney Creek 11,Reach-1,7
Up Type=0
Dn Type=3
Dn Slope=0.005

--- Chimney Creek 1172.g01 (geometry) ---

Geom Title=Existing Conditions

River Reach=Chimney Creek 11,Reach-1
Reach XY= 30
      1647105.00      7014738.00      1647349.48      7015035.57
      1647508.55      7015536.53      1647618.63      7015701.21
      1648188.32      7016271.36      1648464.68      7016398.76
      1648895.21      7016827.48      1649180.11      7016888.15
      1649360.53      7016790.37      1649499.06      7016790.25
      1649957.42      7016943.54      1650432.14      7017314.47
      1650504.48      7017553.22      1650508.75      7018036.45
      1650665.52      7018347.79      1650948.94      7018629.86
      1651307.30      7018743.83      1651720.16      7019087.62
      1652039.06      7019087.08      1652456.53      7018841.74
      1652703.54      7018841.54      1652949.46      7019085.63
      1653118.40      7019551.30      1653298.94      7019729.86
      1653560.94      7019835.73      1654199.07      7019935.76
      1654394.49      7019797.81      1654520.30      7019537.81
      1654624.31      7019708.55      1654705.00      7019738.00

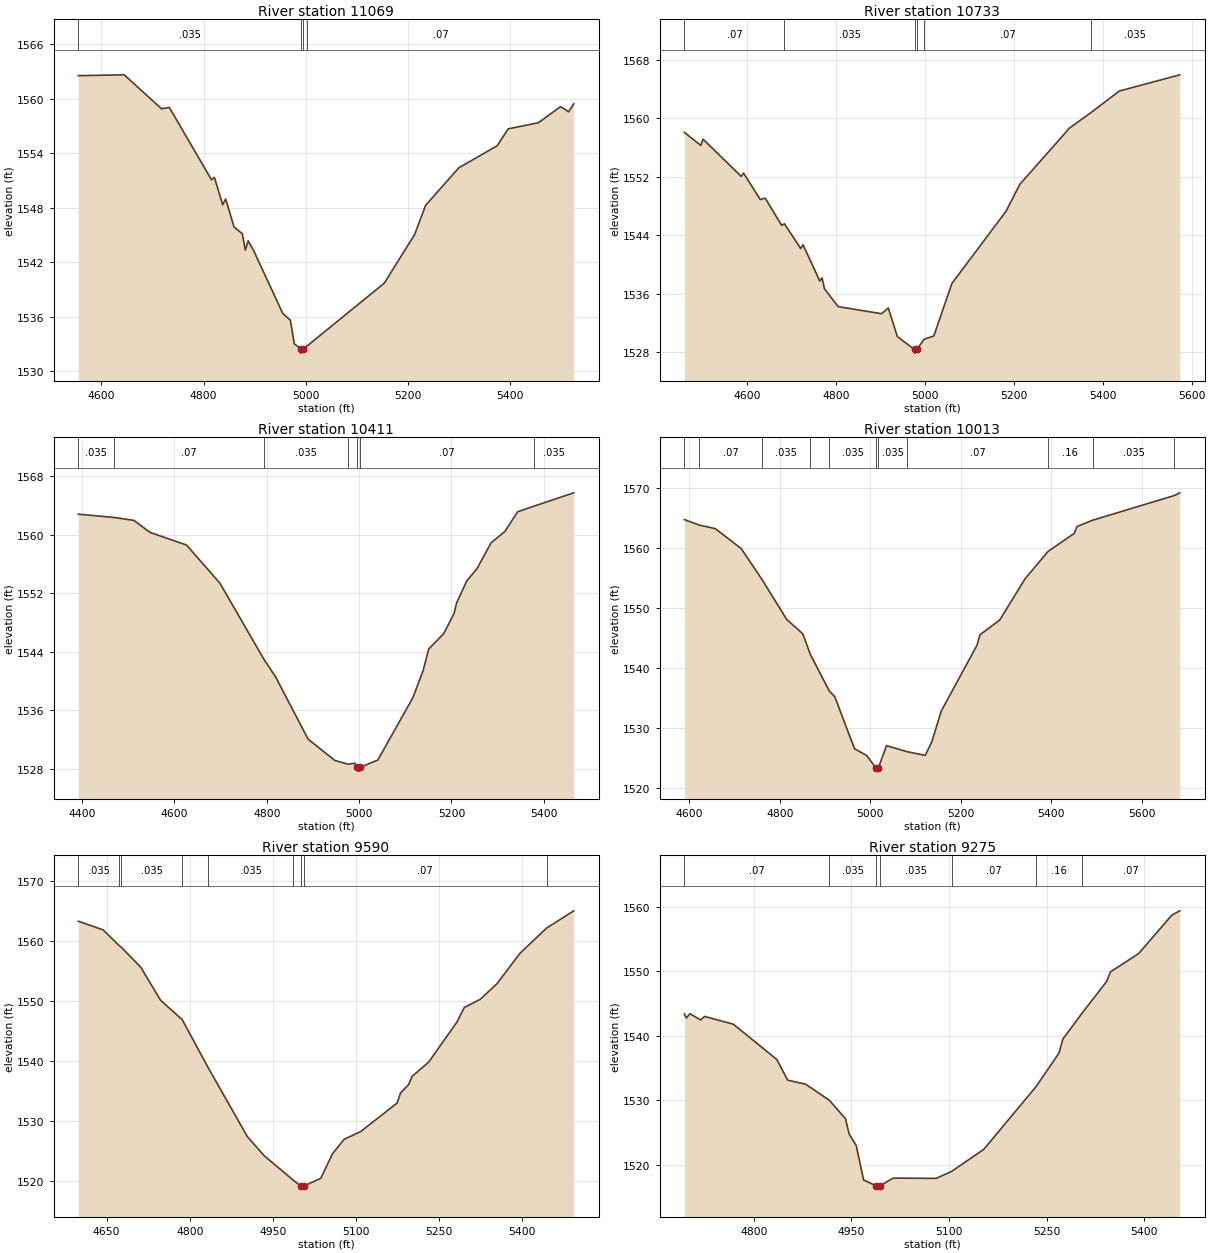
Type RM Length L Ch R = 1,11069,336,336,336
BEGIN DESCRIPTION:
Chimney Creek 1172 24.0
END DESCRIPTION:
XS GIS Cut Line= 3
      1646780.80      7015065.02      1647174.76      7014858.10
      1647631.21      7014599.52
#Sta/Elev= 30
  4555.0 1562.52  4644.9 1562.61  4717.9 1558.87  4733.1 1559.02  4815.7 1551.05
  4821.3 1551.32  4837.7 1548.30  4843.3 1548.94  4859.7 1545.87  4876.0 1545.11
  4881.8 1543.31  4887.4 1544.33  4898.2 1543.25  4955.1 1536.34  4970.0 1535.60
  4977.7 1532.99  4990.0 1532.47  4990.2 1531.97  4994.1 1532.47  5003.5 1532.79
  5153.9 1539.68  5213.1 1545.02  5234.7 1548.24  5299.6 1552.37  5374.7 1554.80
  5396.3 1556.66  5455.5 1557.34  5498.7 1559.11  5514.6 1558.54  5524.6 1559.42
#Mann=4,-1,0
  4555.0   0.035       0  4990.0   0.035       0  4994.1   0.035       0
  5003.5    0.07       0
Bank Sta=4990,4994.1
Exp/Cntr=0.3,0.1

Type RM Length L Ch R = 1,10733,322,322,322
BEGIN DESCRIPTION:
Mapping XS 16eb114d
END DESCRIPTION:
XS GIS Cut Line= 3
      1646827.67      7015242.10      1647351.12      7015122.30
      1647918.60      7015012.97
#Sta/Elev= 30
  4458.5 1558.09  4495.5 1556.31  4500.6 1557.17  4586.5 1552.06  4591.6 1552.52
  4629.4 1548.89  4640.4 1549.09  4677.5 1545.35  4683.6 1545.58  4720.4 1542.18
  4725.5 1542.70  4763.3 1537.73  4768.4 1538.15  4773.8 1536.67  4804.6 1534.22
  4902.4 1533.25  4917.4 1534.04  4937.9 1530.11  4976.4 1528.35  4976.8 1527.85
  4981.4 1528.35  4998.3 1529.76  5019.8 1530.20  5060.5 1537.39  5182.7 1547.32
  5213.3 1550.97  5325.3 1558.69  5372.9 1560.78  5437.3 1563.76  5573.4 1565.98
#Mann=6,-1,0
  4458.5    0.07       0  4683.6   0.035       0  4976.4    0.07       0
  4981.4   0.035       0  4998.3    0.07       0  5372.9   0.035       0
Bank Sta=4976.4,4981.4
Exp/Cntr=0.3,0.1

Type RM Length L Ch R = 1,10411,398,398,398
BEGIN DESCRIPTION:
Mapping XS 298012f4
END DESCRIPTION:
XS GIS Cut Line= 3
      1647022.99      7015765.53      1647502.16      7015390.53
      1647913.59      7015174.40
#Sta/Elev= 30
  4391.9 1562.80  4469.8 1562.35  4512.3 1561.95  4547.6 1560.30  4626.3 1558.59
  4698.6 1553.37  4794.6 1542.90  4818.9 1540.60  4889.7 1532.05  4947.3 1529.15
  4975.9 1528.63  4990.6 1528.76  4996.5 1528.18  4996.8 1527.68  5001.1 1527.68
  5001.5 1528.18  5040.6 1529.19  5116.5 1537.70  5139.1 1541.48  5150.8 1544.36
  5183.6 1546.49  5205.7 1549.20  5211.3 1550.67  5233.4 1553.69  5255.4 1555.34
  5286.0 1558.89  5315.9 1560.44  5343.6 1563.13  5378.4 1563.89  5465.1 1565.72
#Mann=7,-1,0
  4391.9   0.035       0  4469.8    0.07       0  4794.6   0.035       0
  4975.9    0.07       0  4996.5    0.07       0  5001.5    0.07       0
  5378.4   0.035       0
Bank Sta=4996.5,5001.5
Exp/Cntr=0.3,0.1

Type RM Length L Ch R = 1,10013,423,423,423
BEGIN DESCRIPTION:
Mapping XS 5d21b315
END DESCRIPTION:
XS GIS Cut Line= 3
      1647325.07      7015984.29      1647653.20      7015734.28
      1648200.05      7015325.45
#Sta/Elev= 30
  4589.1 1564.70  4621.6 1563.80  4657.7 1563.19  4714.7 1559.88  4760.0 1554.81
  4815.3 1548.08  4851.0 1545.67  4867.6 1542.25  4909.5 1536.16  4921.7 1535.19
  4965.3 1526.53  4992.4 1525.41  5012.8 1523.31  5013.1 1522.81  5017.8 1523.31
  5036.1 1527.05  5081.8 1526.04  5121.6 1525.44  5136.2 1527.70  5157.0 1532.81
  5236.2 1543.80  5242.5 1545.51  5286.2 1547.97  5342.5 1554.86  5393.0 1559.39
  5450.9 1562.40  5457.1 1563.55  5491.9 1564.60  5672.6 1568.72  5684.4 1569.16
#Mann=11,-1,0
  4589.1   0.035       0  4621.6    0.07       0  4760.0   0.035       0
  4867.6    0.07       0  4909.5   0.035       0  5012.8   0.035       0
  5017.8   0.035       0  5081.8    0.07       0  5393.0    0.16       0
  5491.9   0.035       0  5672.6    0.07       0
Bank Sta=5012.8,5017.8
Exp/Cntr=0.3,0.1

Type RM Length L Ch R = 1,9590,315,315,315
BEGIN DESCRIPTION:
Mapping XS 15e2e846
END DESCRIPTION:
XS GIS Cut Line= 3
      1647585.48      7016210.85      1647944.87      7016020.74
      1648348.50      7015747.31
#Sta/Elev= 30
  4599.0 1563.37  4643.7 1561.92  4672.8 1559.29  4675.9 1559.07  4711.6 1555.69
  4747.6 1550.15  4786.5 1546.92  4833.8 1538.83  4903.9 1527.41  4934.4 1524.19
  4985.9 1520.19  5000.6 1519.11  5001.0 1518.61  5005.7 1519.11  5036.6 1520.42
  5057.6 1524.50  5078.6 1526.92  5108.5 1528.23  5174.3 1532.98  5180.4 1534.66
  5195.3 1536.10  5201.4 1537.45  5231.3 1539.83  5282.2 1546.51  5295.6 1548.96
  5324.1 1550.31  5354.1 1552.88  5396.0 1558.00  5444.0 1562.21  5493.1 1565.10
#Mann=9,-1,0
  4599.0   0.035       0  4672.8    0.07       0  4675.9   0.035       0
  4786.5    0.07       0  4833.8   0.035       0  4985.9    0.07       0
  5000.6    0.07       0  5005.7    0.07       0  5444.0    0.16       0
Bank Sta=5000.6,5005.7
Exp/Cntr=0.3,0.1

Type RM Length L Ch R = 1,9275,437,437,437
BEGIN DESCRIPTION:
Mapping XS 33b99da8
END DESCRIPTION:
XS GIS Cut Line= 3
      1647889.69      7016385.57      1648160.49      7016247.56
      1648548.48      7016005.40
#Sta/Elev= 30
  4693.4 1543.40  4696.4 1542.78  4702.0 1543.44  4718.6 1542.47  4724.3 1543.02
  4768.7 1541.81  4835.4 1536.35  4852.1 1533.14  4879.9 1532.50  4916.1 1530.02
  4941.0 1527.16  4946.6 1524.77  4957.5 1522.99  4968.8 1517.65  4988.6 1516.73
  4989.0 1516.23  4993.7 1516.73  5014.4 1517.94  5080.4 1517.90  5104.2 1518.99
  5153.5 1522.40  5233.9 1532.14  5269.1 1537.34  5275.0 1539.50  5305.1 1543.60
  5342.3 1548.45  5348.2 1549.93  5391.7 1552.79  5442.5 1558.74  5454.7 1559.40
#Mann=7,-1,0
  4693.4    0.07       0  4916.1   0.035       0  4988.6   0.035       0
  4993.7   0.035       0  5104.2    0.07       0  5233.9    0.16       0
  5305.1    0.07       0
Bank Sta=4988.6,4993.7
Exp/Cntr=0.3,0.1

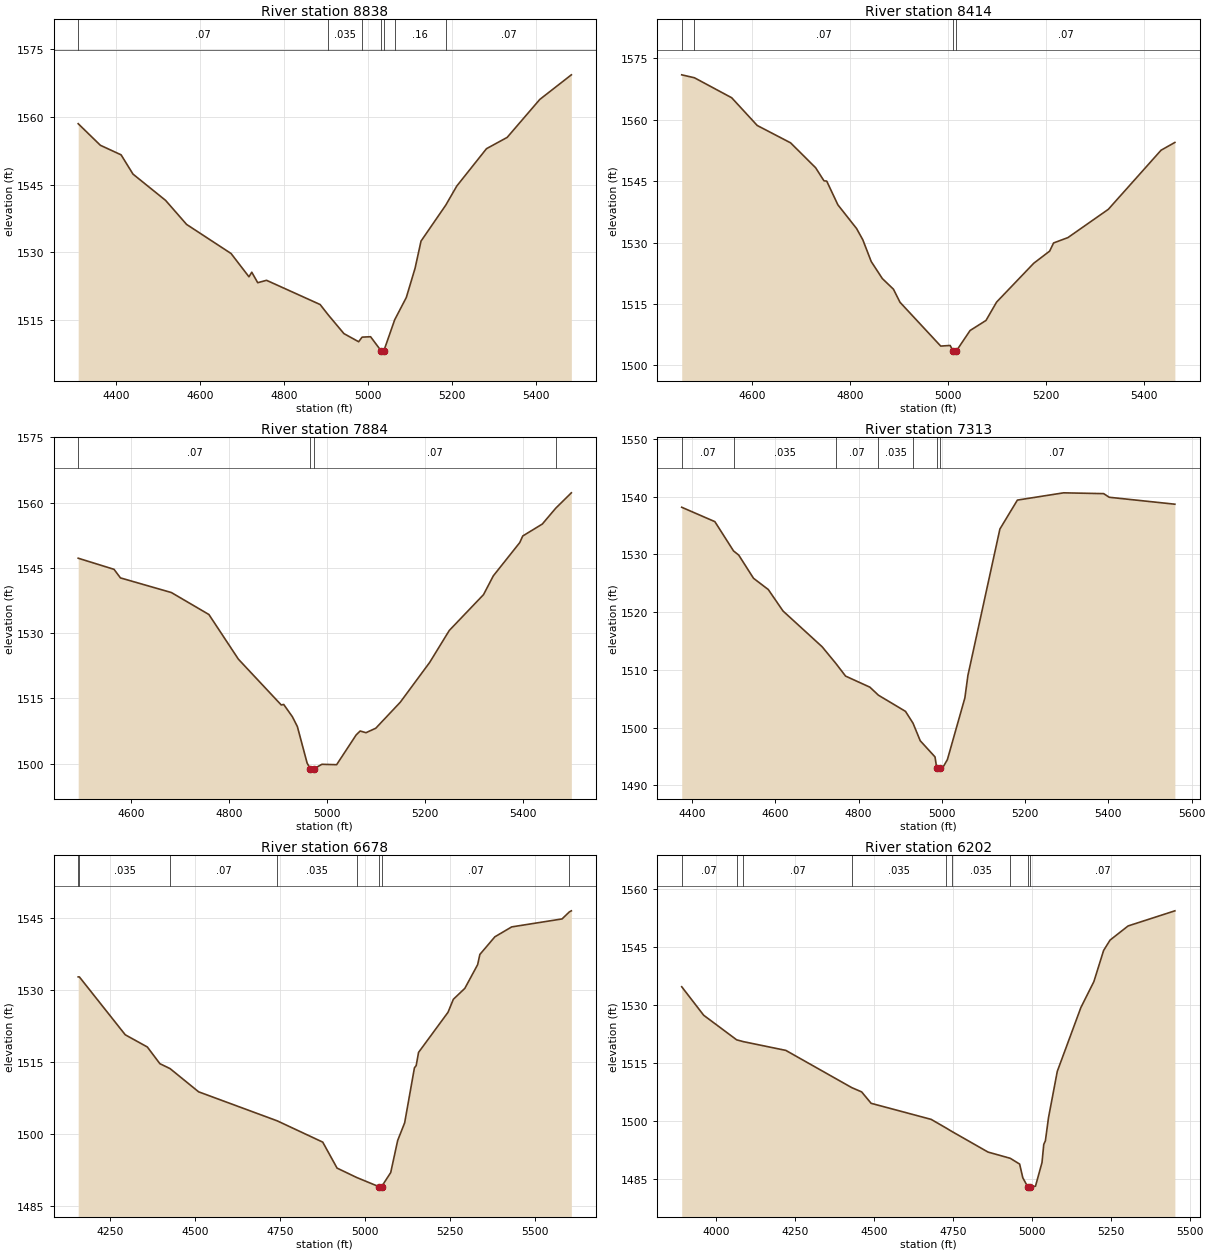
Type RM Length L Ch R = 1,8838,424,424,424
BEGIN DESCRIPTION:
Mapping XS d41bd91a
END DESCRIPTION:
XS GIS Cut Line= 3
      1648061.53      7016968.93      1648525.08      7016461.11
      1648855.22      7016102.37
#Sta/Elev= 30
  4310.2 1558.50  4363.1 1553.72  4412.4 1551.61  4440.8 1547.34  4518.5 1541.52
  4568.4 1536.21  4674.5 1529.76  4717.1 1524.61  4723.8 1525.62  4738.0 1523.30
  4759.0 1523.83  4886.7 1518.47  4905.8 1516.20  4943.4 1512.03  4978.5 1510.23
  4986.7 1511.25  5006.9 1511.34  5032.1 1508.21  5032.6 1507.71  5038.5 1508.21
  5064.3 1515.08  5092.0 1520.02  5113.0 1526.53  5127.1 1532.51  5186.2 1540.49
  5212.2 1544.69  5283.1 1552.97  5332.4 1555.47  5410.1 1563.87  5485.3 1569.32
#Mann=7,-1,0
  4310.2    0.07       0  4905.8   0.035       0  4986.7    0.07       0
  5032.1    0.07       0  5038.5    0.07       0  5064.3    0.16       0
  5186.2    0.07       0
Bank Sta=5032.1,5038.5
Exp/Cntr=0.3,0.1

Type RM Length L Ch R = 1,8414,530,530,530
BEGIN DESCRIPTION:
Mapping XS 34ee2dde
END DESCRIPTION:
XS GIS Cut Line= 3
      1648592.81      7017250.13      1648827.16      7016757.98
      1649003.81      7016331.95
#Sta/Elev= 30
  4456.6 1570.94  4482.6 1570.22  4558.6 1565.34  4610.7 1558.57  4678.8 1554.33
  4729.8 1548.26  4746.9 1545.06  4752.5 1544.99  4775.2 1539.21  4813.4 1533.41
  4826.1 1530.67  4843.3 1525.35  4866.0 1521.19  4888.7 1518.59  4902.0 1515.41
  4985.1 1504.71  5004.4 1504.86  5010.3 1503.49  5010.8 1502.99  5016.8 1503.49
  5045.0 1508.51  5077.5 1510.97  5099.1 1515.45  5174.9 1524.93  5207.4 1527.90
  5215.4 1529.89  5244.7 1531.20  5327.1 1538.10  5434.7 1552.53  5462.9 1554.43
#Mann=4,-1,0
  4456.6   0.035       0  4482.6    0.07       0  5010.3    0.07       0
  5016.8    0.07       0
Bank Sta=5010.3,5016.8
Exp/Cntr=0.3,0.1

Type RM Length L Ch R = 1,7884,571,571,571
BEGIN DESCRIPTION:
Mapping XS b51e8116
END DESCRIPTION:
XS GIS Cut Line= 3
      1649233.41      7017343.94      1649277.68      7016841.31
      1649293.31      7016338.72
#Sta/Elev= 30
  4492.1 1547.23  4565.3 1544.67  4578.4 1542.70  4682.5 1539.33  4759.1 1534.28
  4819.3 1524.01  4906.9 1513.47  4911.9 1513.59  4929.7 1510.75  4939.8 1508.51
  4959.8 1500.08  4966.6 1498.75  4967.1 1498.25  4973.1 1498.75  4990.0 1499.82
  5020.0 1499.73  5060.0 1506.59  5068.1 1507.48  5080.0 1507.09  5100.0 1508.12
  5150.1 1514.11  5210.1 1523.26  5250.1 1530.60  5320.1 1538.85  5340.1 1543.17
  5394.1 1550.82  5400.2 1552.34  5440.2 1555.09  5467.5 1558.72  5499.5 1562.27
#Mann=4,-1,0
  4492.1    0.07       0  4966.6    0.07       0  4973.1    0.07       0
  5467.5    0.16       0
Bank Sta=4966.6,4973.1
Exp/Cntr=0.3,0.1

Type RM Length L Ch R = 1,7313,635,635,635
BEGIN DESCRIPTION:
Mapping XS bd1f19db
END DESCRIPTION:
XS GIS Cut Line= 3
      1649427.41      7017391.85      1649799.82      7016891.83
      1649971.69      7016357.98
#Sta/Elev= 30
  4375.4 1538.16  4455.0 1535.67  4499.8 1530.60  4512.4 1529.87  4547.8 1525.86
  4583.3 1523.91  4618.7 1520.19  4712.6 1514.00  4745.8 1511.09  4768.9 1508.92
  4827.3 1507.00  4847.8 1505.61  4912.8 1502.81  4930.9 1500.76  4948.2 1497.72
  4983.7 1494.92  4987.9 1492.96  4988.4 1492.46  4994.0 1492.46  4994.5 1492.96
  5003.8 1493.26  5013.4 1494.45  5055.4 1505.14  5062.7 1509.04  5139.5 1534.39
  5181.5 1539.40  5292.5 1540.66  5388.7 1540.52  5402.1 1539.89  5559.7 1538.69
#Mann=7,-1,0
  4375.4    0.07       0  4499.8   0.035       0  4745.8    0.07       0
  4847.8   0.035       0  4930.9    0.07       0  4987.9    0.07       0
  4994.5    0.07       0
Bank Sta=4987.9,4994.5
Exp/Cntr=0.3,0.1

Type RM Length L Ch R = 1,6678,476,476,476
BEGIN DESCRIPTION:
Mapping XS e592bb07
END DESCRIPTION:
XS GIS Cut Line= 3
      1649500.39      7017399.64      1650320.65      7017204.33
      1650914.40      7017076.73
#Sta/Elev= 30
  4156.2 1532.67  4159.6 1532.67  4294.6 1520.61  4359.5 1518.07  4396.5 1514.59
  4426.5 1513.56  4510.4 1508.73  4741.7 1502.68  4875.5 1498.25  4917.6 1492.84
  4975.4 1490.88  5041.2 1488.96  5041.7 1488.46  5048.4 1488.96  5075.4 1491.91
  5095.9 1498.60  5116.4 1502.27  5145.2 1513.73  5150.3 1514.19  5157.3 1516.94
  5244.0 1525.30  5259.6 1528.00  5293.3 1530.27  5331.1 1535.22  5337.6 1537.34
  5381.8 1541.02  5431.2 1543.08  5579.3 1544.74  5600.9 1546.21  5606.7 1546.43
#Mann=8,-1,0
  4156.2    0.07       0  4159.6   0.035       0  4426.5    0.07       0
  4741.7   0.035       0  4975.4    0.07       0  5041.2    0.07       0
  5048.4    0.07       0  5600.9   0.035       0
Bank Sta=5041.2,5048.4
Exp/Cntr=0.3,0.1

Type RM Length L Ch R = 1,6202,235,235,235
BEGIN DESCRIPTION:
Mapping XS 516d0f4d
END DESCRIPTION:
XS GIS Cut Line= 3
      1649395.38      7017600.95      1650504.77      7017611.37
      1650944.86      7017509.80
#Sta/Elev= 30
  3890.1 1534.79  3959.7 1527.40  4064.2 1521.03  4085.2 1520.57  4219.7 1518.30
  4428.3 1508.66  4459.7 1507.55  4489.7 1504.59  4679.8 1500.43  4728.0 1498.15
  4744.2 1497.35  4859.8 1491.96  4930.0 1490.35  4959.8 1488.85  4969.8 1485.31
  4986.1 1482.86  4986.6 1482.36  4993.4 1482.86  5010.0 1483.13  5030.6 1489.25
  5036.2 1493.96  5041.3 1494.87  5051.1 1500.84  5079.0 1512.87  5153.7 1529.41
  5194.8 1536.12  5225.6 1544.19  5246.1 1546.88  5303.1 1550.54  5451.2 1554.46
#Mann=9,-1,0
  3890.1    0.07       0  4064.2   0.035       0  4085.2    0.07       0
  4428.3   0.035       0  4728.0    0.07       0  4744.2   0.035       0
  4930.0    0.07       0  4986.1    0.07       0  4993.4    0.07       0
Bank Sta=4986.1,4993.4
Exp/Cntr=0.3,0.1

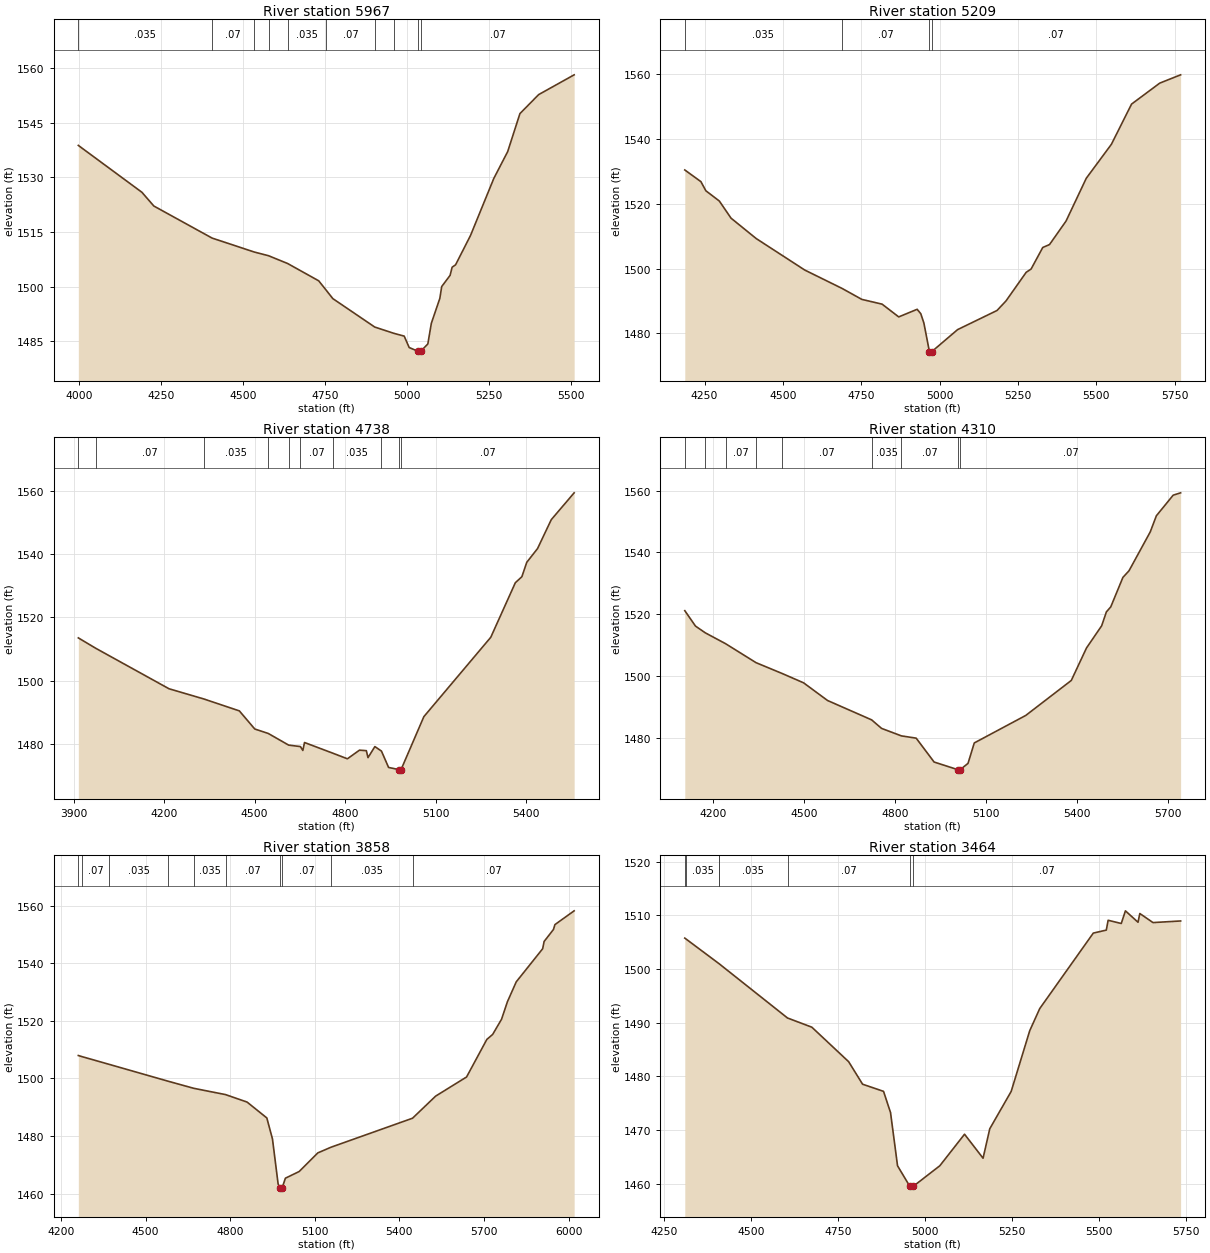
Type RM Length L Ch R = 1,5967,758,758,758
BEGIN DESCRIPTION:
Mapping XS 8bfe3a27
END DESCRIPTION:
XS GIS Cut Line= 3
      1649575.06      7018218.14      1650496.95      7017848.35
      1650986.52      7017679.08
#Sta/Elev= 30
  3998.2 1538.77  4192.1 1525.89  4228.3 1522.13  4405.7 1513.33  4534.5 1509.49
  4577.9 1508.48  4635.9 1506.35  4730.8 1501.59  4753.7 1499.01  4773.9 1496.70
  4901.7 1488.89  4960.2 1487.16  4991.5 1486.40  5006.6 1483.27  5033.8 1482.23
  5034.3 1481.73  5041.7 1482.23  5063.5 1484.25  5074.2 1489.92  5100.1 1496.77
  5105.8 1500.01  5131.3 1503.08  5137.6 1505.32  5148.1 1505.99  5193.6 1514.04
  5264.5 1529.68  5306.9 1537.07  5344.2 1547.50  5401.2 1552.71  5509.5 1558.15
#Mann=10,-1,0
  3998.2   0.035       0  4405.7    0.07       0  4534.5   0.035       0
  4577.9    0.07       0  4635.9   0.035       0  4753.7    0.07       0
  4901.7   0.035       0  4960.2    0.07       0  5033.8    0.07       0
  5041.7    0.07       0
Bank Sta=5033.8,5041.7
Exp/Cntr=0.3,0.1

Type RM Length L Ch R = 1,5209,471,471,471
BEGIN DESCRIPTION:
Mapping XS 2e648fce
END DESCRIPTION:
XS GIS Cut Line= 3
      1650103.76      7018897.80      1650804.24      7018491.57
      1651470.45      7018101.22
#Sta/Elev= 30
  4187.1 1530.48  4238.5 1526.87  4254.3 1524.05  4297.3 1520.88  4334.6 1515.59
  4414.9 1509.29  4569.8 1499.56  4688.8 1493.88  4752.0 1490.49  4816.6 1489.02
  4869.6 1485.08  4928.4 1487.43  4940.0 1486.07  4949.9 1483.19  4967.5 1474.39
  4968.0 1473.89  4975.5 1474.39  5057.4 1481.15  5183.2 1487.06  5211.9 1490.02
  5276.3 1498.86  5292.0 1499.88  5329.2 1506.53  5350.7 1507.43  5403.4 1514.68
  5468.0 1527.91  5548.1 1538.40  5612.5 1550.83  5702.5 1557.31  5769.0 1559.87
#Mann=4,-1,0
  4187.1   0.035       0  4688.8    0.07       0  4967.5    0.07       0
  4975.5    0.07       0
Bank Sta=4967.5,4975.5
Exp/Cntr=0.3,0.1

Type RM Length L Ch R = 1,4738,428,428,428
BEGIN DESCRIPTION:
Mapping XS 2f41b646
END DESCRIPTION:
XS GIS Cut Line= 3
      1650740.34      7019672.08      1651201.29      7018695.48
      1651474.08      7018201.86
#Sta/Elev= 30
  3915.8 1513.50  3974.2 1510.18  4216.5 1497.41  4331.7 1494.19  4449.7 1490.41
  4500.8 1484.68  4545.4 1483.28  4613.1 1479.59  4652.2 1479.12  4660.2 1477.90
  4665.7 1480.41  4759.1 1477.05  4807.9 1475.26  4847.9 1477.99  4870.7 1477.83
  4876.2 1475.63  4899.0 1479.12  4920.8 1477.70  4944.5 1472.52  4977.8 1471.86
  4978.3 1471.36  4985.9 1471.86  5061.4 1488.59  5283.3 1513.70  5364.7 1530.95
  5386.4 1532.85  5402.5 1537.39  5438.4 1541.76  5483.8 1550.89  5559.7 1559.38
#Mann=10,-1,0
  3915.8   0.035       0  3974.2    0.07       0  4331.7   0.035       0
  4545.4    0.07       0  4613.1   0.035       0  4652.2    0.07       0
  4759.1   0.035       0  4920.8    0.07       0  4977.8    0.07       0
  4985.9    0.07       0
Bank Sta=4977.8,4985.9
Exp/Cntr=0.3,0.1

Type RM Length L Ch R = 1,4310,452,452,452
BEGIN DESCRIPTION:
Mapping XS 61509adc
END DESCRIPTION:
XS GIS Cut Line= 3
      1651435.67      7019825.64      1651537.23      7018942.88
      1651571.09      7018198.04
#Sta/Elev= 30
  4107.2 1521.13  4142.6 1516.12  4174.9 1513.94  4241.7 1510.42  4342.1 1504.27
  4428.4 1500.75  4498.7 1497.74  4577.7 1492.01  4723.0 1485.73  4755.8 1482.96
  4821.1 1480.54  4869.8 1479.80  4928.9 1472.06  5006.2 1469.61  5006.7 1469.11
  5015.2 1469.61  5040.7 1471.63  5061.3 1478.25  5230.9 1487.16  5381.1 1498.51
  5431.1 1509.03  5481.2 1516.24  5496.7 1520.73  5511.2 1522.38  5551.2 1531.92
  5571.3 1534.07  5641.3 1546.67  5661.4 1551.89  5716.9 1558.58  5741.4 1559.34
#Mann=9,-1,0
  4107.2    0.07       0  4174.9   0.035       0  4241.7    0.07       0
  4342.1   0.035       0  4428.4    0.07       0  4723.0   0.035       0
  4821.1    0.07       0  5006.2    0.07       0  5015.2    0.07       0
Bank Sta=5006.2,5015.2
Exp/Cntr=0.3,0.1

Type RM Length L Ch R = 1,3858,394,394,394
BEGIN DESCRIPTION:
Mapping XS d4897a33
END DESCRIPTION:
XS GIS Cut Line= 3
      1651966.92      7019825.64      1651933.06      7019091.31
      1651639.32      7018111.30
#Sta/Elev= 30
  4261.5 1507.97  4273.8 1507.60  4371.9 1504.87  4578.0 1499.09  4670.4 1496.58
  4783.5 1494.38  4859.8 1491.79  4929.9 1486.27  4949.9 1478.97  4969.9 1463.37
  4975.4 1462.02  4975.9 1461.52  4984.5 1462.02  4995.8 1465.32  5044.6 1467.64
  5110.7 1474.11  5156.7 1476.06  5446.6 1486.17  5528.5 1493.85  5638.2 1500.51
  5710.0 1513.55  5730.8 1515.31  5762.2 1520.57  5783.0 1526.65  5814.4 1533.59
  5908.0 1545.08  5913.2 1547.62  5946.3 1551.78  5951.5 1553.48  6019.7 1558.27
#Mann=10,-1,0
  4261.5   0.035       0  4273.8    0.07       0  4371.9   0.035       0
  4578.0    0.07       0  4670.4   0.035       0  4783.5    0.07       0
  4975.4    0.07       0  4984.5    0.07       0  5156.7   0.035       0
  5446.6    0.07       0
Bank Sta=4975.4,4984.5
Exp/Cntr=0.3,0.1

Type RM Length L Ch R = 1,3464,415,415,415
BEGIN DESCRIPTION:
Mapping XS 55a9de3b
END DESCRIPTION:
XS GIS Cut Line= 3
      1652320.39      7019627.04      1652263.10      7018942.18
      1652427.16      7018223.42
#Sta/Elev= 30
  4310.3 1505.74  4314.2 1505.55  4408.5 1500.98  4408.7 1500.97  4605.4 1490.85
  4675.2 1489.14  4781.0 1482.71  4821.1 1478.51  4881.3 1477.18  4901.4 1473.22
  4921.5 1463.31  4957.0 1459.46  4957.5 1458.96  4966.2 1459.46  5042.9 1463.31
  5114.0 1469.19  5167.2 1464.72  5186.5 1470.21  5248.0 1477.17  5301.3 1488.48
  5330.1 1492.61  5483.9 1506.67  5521.3 1507.23  5526.5 1509.06  5564.3 1508.46
  5576.2 1510.82  5612.4 1508.69  5617.6 1510.32  5655.4 1508.63  5734.8 1508.93
#Mann=7,-1,0
  4310.3    0.07       0  4314.2   0.035       0  4408.5    0.07       0
  4408.7   0.035       0  4605.4    0.07       0  4957.0    0.07       0
  4966.2    0.07       0
Bank Sta=4957,4966.2
Exp/Cntr=0.3,0.1

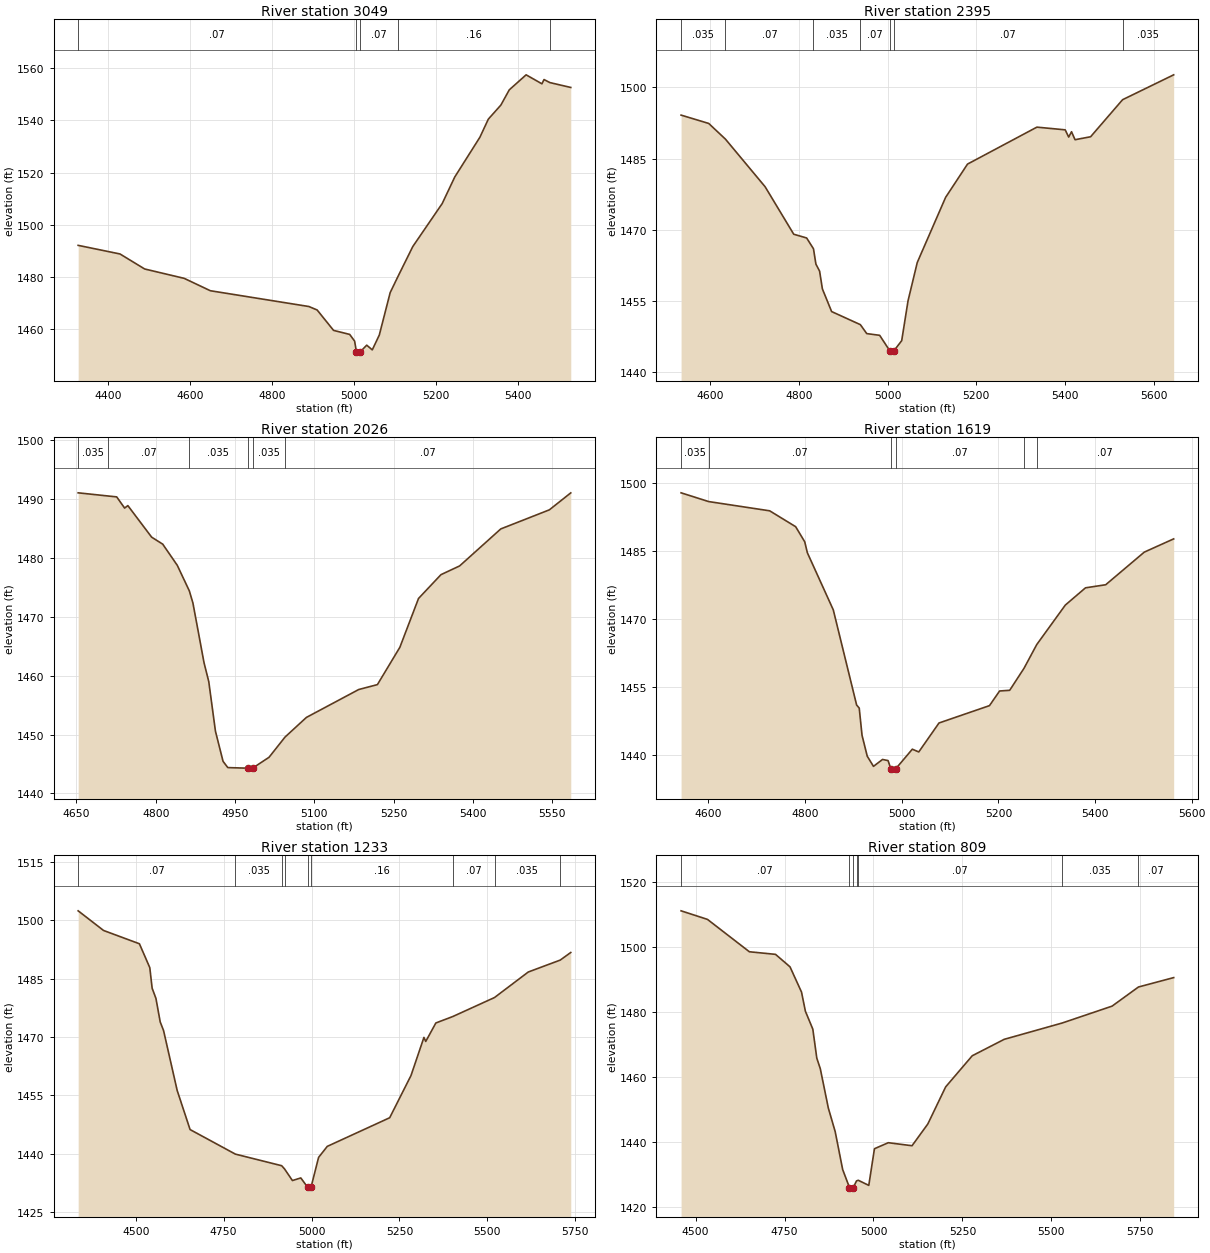
Type RM Length L Ch R = 1,3049,654,654,654
BEGIN DESCRIPTION:
Mapping XS 08017519
END DESCRIPTION:
XS GIS Cut Line= 3
      1652580.81      7019509.87      1652630.29      7018840.62
      1652744.51      7018321.41
#Sta/Elev= 30
  4326.0 1492.16  4428.1 1488.87  4488.3 1483.13  4584.9 1479.54  4648.7 1474.81
  4889.4 1468.77  4909.5 1467.44  4949.6 1459.64  4988.9 1458.11  5001.0 1455.54
  5005.3 1451.45  5005.8 1450.95  5014.7 1451.45  5030.5 1453.99  5044.1 1452.20
  5061.2 1457.85  5087.8 1474.09  5106.7 1480.22  5143.1 1491.73  5214.8 1508.14
  5245.5 1518.31  5306.9 1533.52  5327.4 1540.42  5358.1 1545.81  5378.6 1551.63
  5419.7 1557.37  5458.3 1553.93  5463.4 1555.56  5477.8 1554.40  5528.7 1552.54
#Mann=5,-1,0
  4326.0    0.07       0  5005.3    0.07       0  5014.7    0.07       0
  5106.7    0.16       0  5477.8    0.07       0
Bank Sta=5005.3,5014.7
Exp/Cntr=0.3,0.1

Type RM Length L Ch R = 1,2395,369,369,369
BEGIN DESCRIPTION:
Mapping XS e848ae9e
END DESCRIPTION:
XS GIS Cut Line= 3
      1652729.24      7019658.34      1653010.49      7019283.33
      1653505.27      7018874.49
#Sta/Elev= 30
  4534.3 1494.17  4596.6 1492.41  4634.4 1489.09  4723.7 1479.06  4788.3 1469.03
  4817.4 1468.24  4832.8 1465.96  4838.3 1462.72  4846.6 1461.24  4852.9 1457.49
  4873.7 1452.71  4938.5 1449.95  4952.9 1448.06  4982.0 1447.70  5004.8 1444.44
  5005.3 1443.94  5014.2 1444.44  5031.7 1446.57  5046.0 1454.99  5066.8 1463.07
  5130.7 1476.81  5180.1 1483.83  5336.5 1491.63  5400.3 1491.06  5408.2 1489.54
  5414.6 1490.66  5422.5 1488.98  5457.6 1489.60  5529.7 1497.42  5644.9 1502.67
#Mann=7,-1,0
  4534.3   0.035       0  4634.4    0.07       0  4832.8   0.035       0
  4938.5    0.07       0  5004.8    0.07       0  5014.2    0.07       0
  5529.7   0.035       0
Bank Sta=5004.8,5014.2
Exp/Cntr=0.3,0.1

Type RM Length L Ch R = 1,2026,407,407,407
BEGIN DESCRIPTION:
Mapping XS f9d37be0
END DESCRIPTION:
XS GIS Cut Line= 3
      1652879.16      7019793.40      1653167.35      7019600.69
      1653581.16      7019186.88
#Sta/Elev= 30
  4653.2 1491.05  4709.9 1490.51  4726.1 1490.36  4741.1 1488.46  4747.2 1488.88
  4792.2 1483.52  4813.2 1482.33  4840.7 1478.74  4863.5 1474.40  4870.3 1472.34
  4891.3 1462.20  4900.3 1458.98  4912.9 1450.57  4927.3 1445.45  4936.3 1444.39
  4973.6 1444.29  4974.1 1443.79  4983.1 1444.29  5014.3 1446.14  5044.6 1449.58
  5085.0 1452.91  5184.0 1457.65  5219.3 1458.48  5261.8 1464.82  5297.1 1473.11
  5339.5 1477.15  5374.9 1478.64  5452.7 1484.92  5544.6 1488.16  5585.1 1491.04
#Mann=6,-1,0
  4653.2   0.035       0  4709.9    0.07       0  4863.5   0.035       0
  4973.6   0.035       0  4983.1   0.035       0  5044.6    0.07       0
Bank Sta=4973.6,4983.1
Exp/Cntr=0.3,0.1

Type RM Length L Ch R = 1,1619,386,386,386
BEGIN DESCRIPTION:
Mapping XS 4eda43fa
END DESCRIPTION:
XS GIS Cut Line= 3
      1653332.27      7020215.30      1653502.42      7019793.40
      1653667.36      7019253.45
#Sta/Elev= 30
  4543.3 1497.85  4600.4 1495.92  4726.7 1493.88  4780.4 1490.38  4799.2 1487.05
  4804.6 1484.64  4858.3 1472.03  4906.6 1451.04  4912.0 1450.35  4917.8 1444.36
  4928.6 1439.74  4941.5 1437.50  4960.3 1439.03  4971.7 1438.77  4977.5 1436.95
  4978.0 1436.45  4987.4 1436.95  5021.9 1441.29  5035.2 1440.68  5077.1 1447.07
  5181.6 1450.90  5202.5 1454.13  5223.4 1454.28  5253.0 1459.13  5279.4 1464.37
  5338.5 1473.08  5380.3 1476.89  5422.1 1477.57  5502.0 1484.77  5562.8 1487.69
#Mann=6,-1,0
  4543.3   0.035       0  4600.4    0.07       0  4977.5    0.07       0
  4987.4    0.07       0  5253.0    0.16       0  5279.4    0.07       0
Bank Sta=4977.5,4987.4
Exp/Cntr=0.3,0.1

Type RM Length L Ch R = 1,1233,424,424,424
BEGIN DESCRIPTION:
Mapping XS 802f8e92
END DESCRIPTION:
XS GIS Cut Line= 3
      1654105.72      7020503.17      1653855.72      7019883.39
      1653749.92      7019158.37
#Sta/Elev= 30
  4336.3 1502.40  4408.5 1497.35  4510.5 1493.93  4540.0 1487.80  4546.7 1482.50
  4557.5 1479.88  4569.6 1473.85  4579.1 1471.65  4617.9 1456.22  4654.6 1446.17
  4783.4 1439.86  4915.1 1436.88  4923.3 1436.04  4945.7 1433.06  4969.5 1433.74
  4988.7 1431.36  4989.2 1430.86  4998.6 1431.36  5020.1 1439.02  5044.8 1441.85
  5222.3 1449.21  5282.9 1460.06  5319.7 1469.86  5324.8 1468.82  5353.6 1473.57
  5402.1 1475.24  5520.4 1480.11  5616.4 1486.67  5707.4 1489.74  5737.3 1491.69
#Mann=9,-1,0
  4336.3    0.07       0  4783.4   0.035       0  4915.1    0.07       0
  4923.3    0.16       0  4988.7    0.07       0  4998.6    0.16       0
  5402.1    0.07       0  5520.4   0.035       0  5707.4    0.07       0
Bank Sta=4988.7,4998.6
Exp/Cntr=0.3,0.1

Type RM Length L Ch R = 1,809,542,542,542
BEGIN DESCRIPTION:
Mapping XS c9862c2f
END DESCRIPTION:
XS GIS Cut Line= 3
      1654413.02      7020411.19      1654249.82      7019892.07
      1653867.86      7019143.79
#Sta/Elev= 30
  4459.3 1511.03  4533.4 1508.40  4651.3 1498.44  4724.7 1497.65  4765.4 1493.81
  4797.8 1486.04  4808.6 1480.17  4829.5 1474.66  4840.7 1465.74  4850.5 1462.51
  4873.1 1450.39  4892.4 1443.14  4913.4 1431.48  4932.5 1425.97  4933.0 1425.47
  4943.2 1425.97  4952.3 1427.99  4957.3 1428.19  4986.8 1426.62  5002.7 1437.89
  5041.6 1439.74  5108.3 1438.81  5152.7 1445.50  5202.8 1456.90  5277.5 1466.47
  5367.3 1471.52  5530.3 1476.54  5670.5 1481.73  5744.6 1487.61  5843.6 1490.50
#Mann=7,-1,0
  4459.3    0.07       0  4932.5    0.07       0  4943.2    0.07       0
  4952.3   0.035       0  4957.3    0.07       0  5530.3   0.035       0
  5744.6    0.07       0
Bank Sta=4932.5,4943.2
Exp/Cntr=0.3,0.1

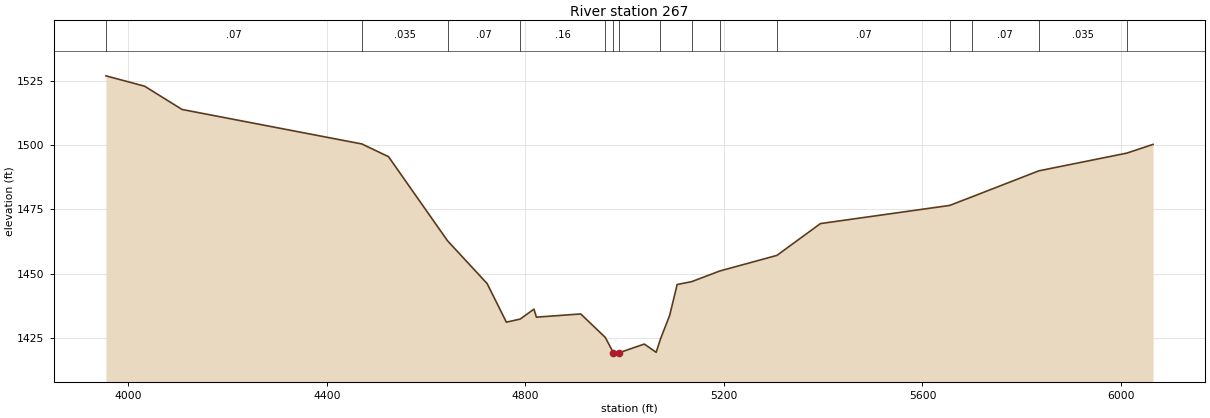
Type RM Length L Ch R = 1,267,0,0,0
BEGIN DESCRIPTION:
Chimney Creek 1172 1.0
END DESCRIPTION:
XS GIS Cut Line= 3
      1654462.08      7020590.69      1654568.61      7019550.93
      1653979.73      7018664.03
#Sta/Elev= 30
  3954.8 1527.02  4032.7 1522.99  4108.3 1513.91  4470.6 1500.47  4524.3 1495.50
  4643.1 1462.76  4722.9 1446.08  4761.7 1431.04  4789.4 1432.24  4817.2 1436.12
  4822.2 1432.99  4911.5 1434.25  4961.0 1425.09  4977.4 1419.09  4977.9 1418.59
  4988.2 1419.09  5039.6 1422.51  5063.5 1419.30  5072.1 1424.46  5090.7 1433.69
  5105.8 1445.71  5135.0 1446.83  5191.7 1450.98  5306.8 1457.06  5394.4 1469.45
  5655.0 1476.53  5699.0 1479.82  5834.6 1490.01  6011.8 1496.91  6064.6 1500.31
#Mann=15,-1,0
  3954.8    0.07       0  4470.6   0.035       0  4643.1    0.07       0
  4789.4    0.16       0  4961.0    0.07       0  4977.4    0.07       0
  4988.2    0.07       0  5072.1    0.16       0  5135.0    0.07       0
  5191.7    0.16       0  5306.8    0.07       0  5655.0   0.035       0
  5699.0    0.07       0  5834.6   0.035       0  6011.8    0.07       0
Bank Sta=4977.4,4988.2
Exp/Cntr=0.3,0.1

Chan Stop Cuts=-1