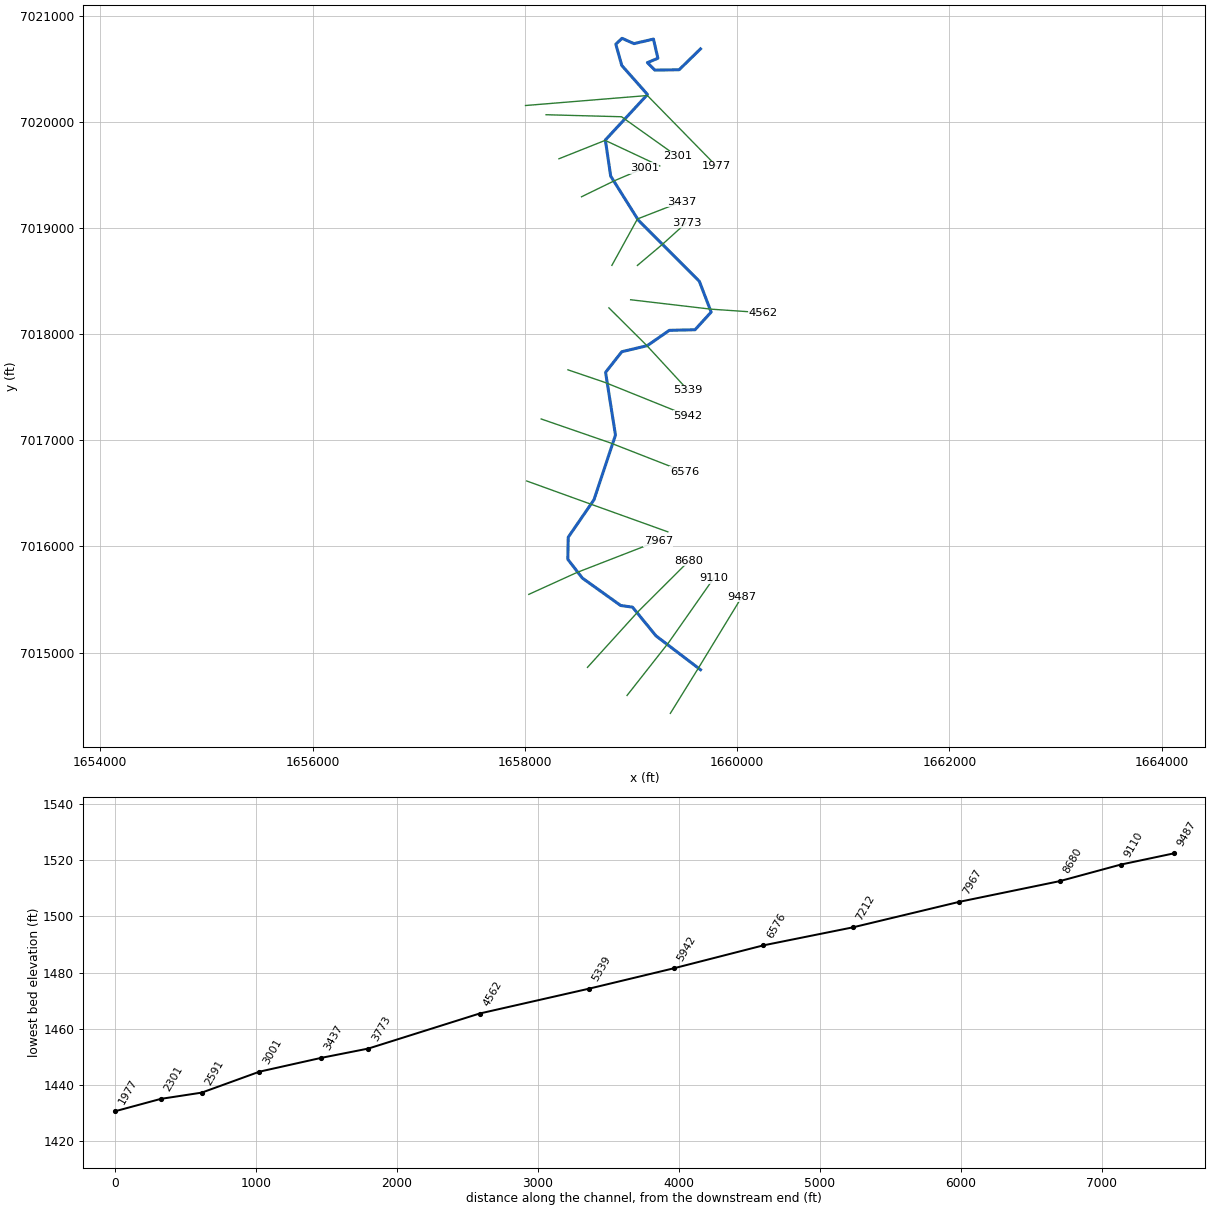
--- Chimney Creek 1173.prj (project) ---

Proj Title=Chimney Creek 1173 Base Level Engineering
Current Plan=p01
Default Exp/Contr=0.3,0.1
English Units
Geom File=g01
Flow File=f01
Plan File=p01
BEGIN DESCRIPTION:
Chimney Creek 1173
END DESCRIPTION:

--- Chimney Creek 1173.p01 (plan) ---

Plan Title=Multiple Run
Short Identifier=Multiple
Geom File=g01
Flow File=f01
Subcritical Flow
K Sum by GR= 0
Std Step Tol= 0.01
Critical Tol= 0.01
Num of Std Step Trials= 20
Max Error Tol= 0.3
Flow Tol Ratio= 0.001
Split Flow NTrial= 30
Split Flow Tol= 0.02
Split Flow Ratio= 0.02
Log Output Level= 0
Friction Slope Method= 1
Unsteady Friction Slope Method= 2
Unsteady Bridges Friction Slope Method= 1
Parabolic Critical Depth
Global Vel Dist=  1 , 1 , 1
Global Log Level= 0
CheckData=True
Encroach Param= -1, 0, 0, 0
BEGIN DESCRIPTION:
Multiple Run
END DESCRIPTION:

--- Chimney Creek 1173.f01 (steady flow) ---

Flow Title=Multiple
Number of Profiles=7
Profile Names=10-year,25-year,50-year,1pct_min,100-year,1pct_plu,500-year
River Rch & RM= Chimney Creek 11,Reach-1,9487
     314     446     558     349     695    1388    1093
River Rch & RM= Chimney Creek 11,Reach-1,7967
     405     579     729     457     911    1818    1442
Boundary for River Rch & Prof#=Chimney Creek 11,Reach-1,1
Up Type=0
Dn Type=3
Dn Slope=0.005
Boundary for River Rch & Prof#=Chimney Creek 11,Reach-1,2
Up Type=0
Dn Type=3
Dn Slope=0.005
Boundary for River Rch & Prof#=Chimney Creek 11,Reach-1,3
Up Type=0
Dn Type=3
Dn Slope=0.005
Boundary for River Rch & Prof#=Chimney Creek 11,Reach-1,4
Up Type=0
Dn Type=3
Dn Slope=0.005
Boundary for River Rch & Prof#=Chimney Creek 11,Reach-1,5
Up Type=0
Dn Type=3
Dn Slope=0.005
Boundary for River Rch & Prof#=Chimney Creek 11,Reach-1,6
Up Type=0
Dn Type=3
Dn Slope=0.005
Boundary for River Rch & Prof#=Chimney Creek 11,Reach-1,7
Up Type=0
Dn Type=3
Dn Slope=0.005

--- Chimney Creek 1173.g01 (geometry) ---

Geom Title=Existing Conditions

River Reach=Chimney Creek 11,Reach-1
Reach XY= 30
      1659655.00      7014838.00      1659234.91      7015157.79
      1659014.81      7015427.49      1658902.57      7015443.52
      1658541.78      7015701.62      1658404.50      7015878.70
      1658408.54      7016086.54      1658651.17      7016439.58
      1658853.78      7017048.51      1658760.46      7017640.45
      1658913.48      7017834.49      1659153.44      7017891.76
      1659360.86      7018035.94      1659603.48      7018041.74
      1659755.11      7018208.08      1659644.24      7018497.68
      1659068.62      7019074.79      1658808.62      7019489.50
      1658758.40      7019829.56      1659155.48      7020258.16
      1658913.14      7020531.94      1658856.89      7020732.34
      1658915.45      7020787.47      1659027.80      7020737.63
      1659211.50      7020780.38      1659253.45      7020599.56
      1659154.33      7020558.45      1659224.85      7020487.93
      1659453.55      7020491.53      1659655.00      7020688.00

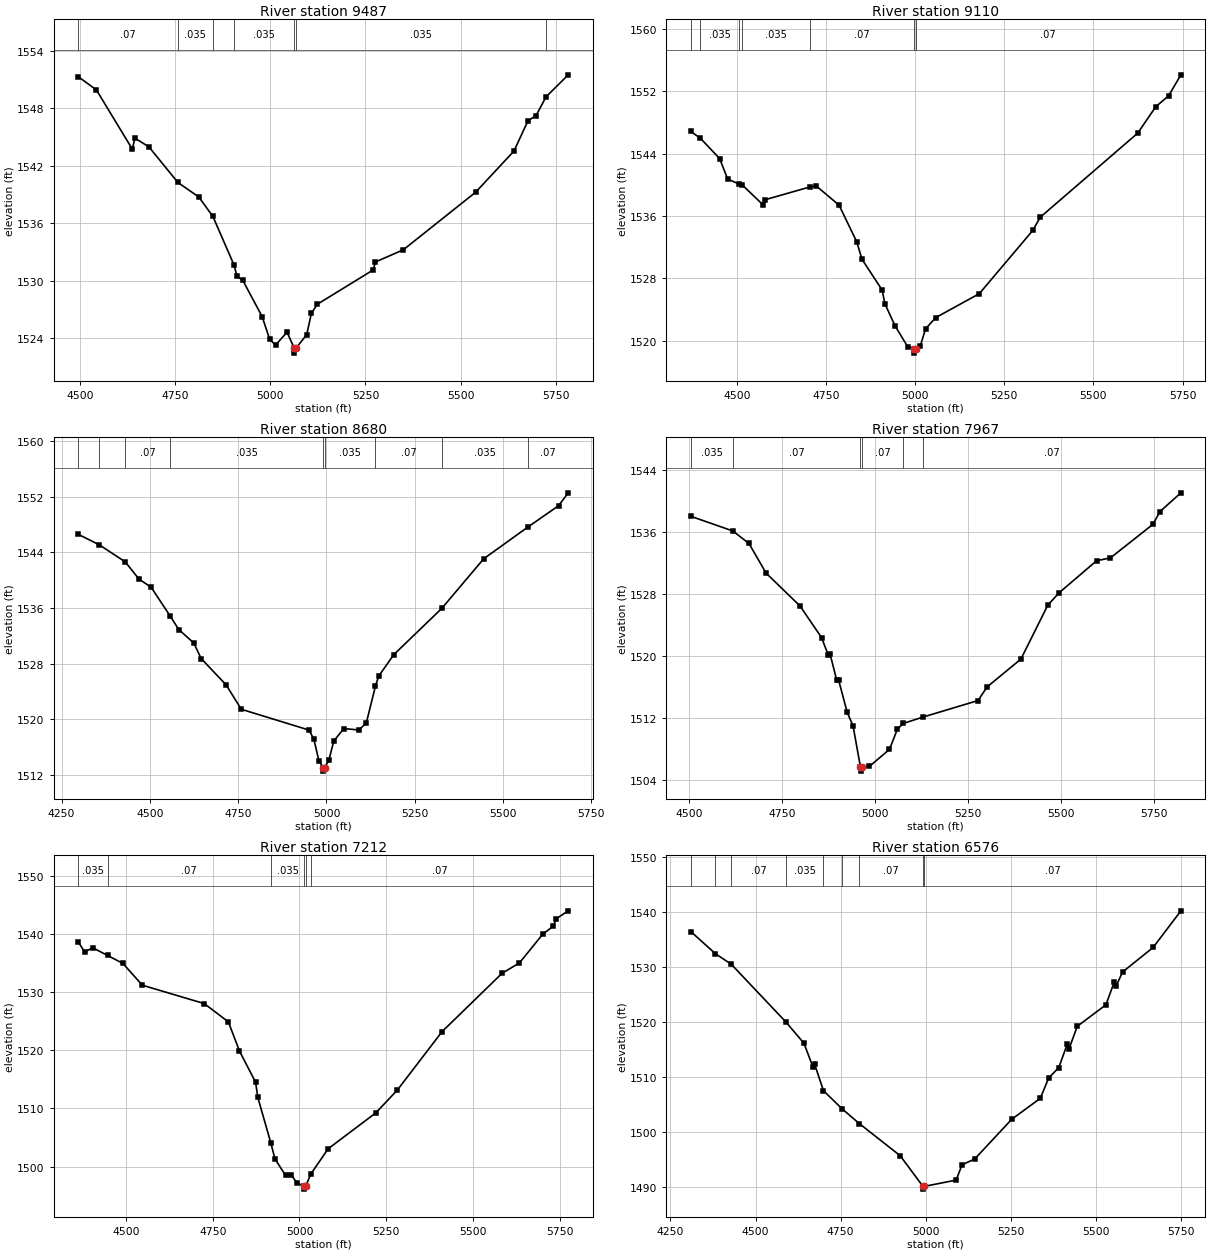
Type RM Length L Ch R = 1,9487,377,377,377
BEGIN DESCRIPTION:
Chimney Creek 1173 19.0
END DESCRIPTION:
XS GIS Cut Line= 3
      1659370.72      7014426.90      1659636.73      7014856.28
      1660044.35      7015524.46
#Sta/Elev= 30
  4494.9 1551.31  4543.2 1549.91  4637.4 1543.73  4644.3 1544.87  4681.0 1543.97
  4757.1 1540.25  4812.1 1538.73  4849.2 1536.70  4904.6 1531.63  4912.5 1530.45
  4927.9 1530.01  4978.5 1526.24  4998.1 1523.90  5013.7 1523.25  5043.9 1524.61
  5063.2 1522.92  5063.4 1522.42  5067.2 1522.92  5095.7 1524.36  5107.8 1526.56
  5123.3 1527.52  5270.3 1531.11  5276.2 1531.94  5349.7 1533.22  5539.5 1539.23
  5640.2 1543.53  5677.0 1546.69  5698.3 1547.24  5724.5 1549.19  5782.7 1551.49
#Mann=7,-1,0
  4494.9    0.07       0  4757.1   0.035       0  4849.2    0.07       0
  4904.6   0.035       0  5063.2   0.035       0  5067.2   0.035       0
  5724.5    0.07       0
Bank Sta=5063.2,5067.2
Exp/Cntr=0.3,0.1

Type RM Length L Ch R = 1,9110,430,430,430
BEGIN DESCRIPTION:
Mapping XS eeb0dc63
END DESCRIPTION:
XS GIS Cut Line= 3
      1658962.71      7014595.68      1659353.32      7015092.19
      1659780.19      7015701.26
#Sta/Elev= 30
  4370.0 1546.83  4397.1 1545.96  4451.1 1543.35  4473.6 1540.73  4504.9 1540.11
  4514.4 1539.98  4573.0 1537.42  4579.4 1538.09  4705.0 1539.73  4722.1 1539.85
  4786.3 1537.38  4836.0 1532.67  4850.4 1530.46  4907.3 1526.49  4914.6 1524.77
  4943.5 1521.90  4978.8 1519.24  4997.1 1518.92  4997.3 1518.42  5001.1 1518.92
  5014.2 1519.34  5029.0 1521.54  5057.7 1522.98  5179.8 1526.04  5329.7 1534.14
  5350.8 1535.84  5624.4 1546.62  5674.9 1550.00  5710.7 1551.39  5745.5 1554.09
#Mann=7,-1,0
  4370.0    0.07       0  4397.1   0.035       0  4504.9    0.07       0
  4514.4   0.035       0  4705.0    0.07       0  4997.1    0.07       0
  5001.1    0.07       0
Bank Sta=4997.1,5001.1
Exp/Cntr=0.3,0.1

Type RM Length L Ch R = 1,8680,713,713,713
BEGIN DESCRIPTION:
Mapping XS deebf532
END DESCRIPTION:
XS GIS Cut Line= 3
      1658590.05      7014860.34      1659063.99      7015382.89
      1659547.13      7015864.29
#Sta/Elev= 30
  4296.8 1546.61  4356.5 1545.10  4430.4 1542.64  4468.9 1540.19  4504.0 1538.97
  4557.5 1534.86  4581.7 1532.92  4624.3 1530.99  4645.2 1528.75  4716.2 1524.95
  4758.8 1521.46  4950.0 1518.48  4964.2 1517.20  4978.4 1514.09  4990.6 1513.07
  4990.9 1512.57  4994.6 1513.07  5006.6 1514.11  5020.7 1516.90  5049.0 1518.69
  5091.4 1518.48  5112.7 1519.47  5138.7 1524.81  5148.0 1526.23  5190.4 1529.30
  5326.4 1535.95  5445.0 1543.08  5571.4 1547.69  5657.1 1550.71  5684.3 1552.56
#Mann=9,-1,0
  4296.8    0.07       0  4356.5   0.035       0  4430.4    0.07       0
  4557.5   0.035       0  4990.6   0.035       0  4994.6   0.035       0
  5138.7    0.07       0  5326.4   0.035       0  5571.4    0.07       0
Bank Sta=4990.6,4994.6
Exp/Cntr=0.3,0.1

Type RM Length L Ch R = 1,7967,755,755,755
BEGIN DESCRIPTION:
Mapping XS 436f37b8
END DESCRIPTION:
XS GIS Cut Line= 3
      1658037.09      7015548.26      1658490.64      7015754.41
      1659256.67      7016051.71
#Sta/Elev= 30
  4503.5 1538.03  4616.7 1536.14  4660.2 1534.53  4706.4 1530.71  4797.8 1526.47
  4855.7 1522.41  4873.3 1520.21  4878.8 1520.28  4896.4 1516.93  4901.9 1516.89
  4924.9 1512.76  4940.6 1511.02  4960.6 1505.70  4960.8 1505.20  4964.6 1505.70
  4984.5 1505.80  5038.6 1508.00  5060.0 1510.61  5075.5 1511.34  5130.0 1512.18
  5277.0 1514.29  5301.6 1516.05  5392.5 1519.63  5465.0 1526.58  5494.9 1528.15
  5596.3 1532.30  5633.7 1532.67  5748.0 1536.99  5767.1 1538.64  5823.4 1541.05
#Mann=6,-1,0
  4503.5   0.035       0  4616.7    0.07       0  4960.6    0.07       0
  4964.6    0.07       0  5075.5   0.035       0  5130.0    0.07       0
Bank Sta=4960.6,4964.6
Exp/Cntr=0.3,0.1

Type RM Length L Ch R = 1,7212,636,636,636
BEGIN DESCRIPTION:
Mapping XS bdb6faab
END DESCRIPTION:
XS GIS Cut Line= 3
      1658017.34      7016616.63      1658612.83      7016401.35
      1659347.25      7016137.44
#Sta/Elev= 30
  4361.5 1538.66  4380.3 1536.89  4404.2 1537.58  4446.7 1536.27  4490.9 1534.90
  4546.9 1531.16  4725.5 1528.00  4795.0 1524.86  4826.9 1519.87  4873.5 1514.48
  4880.0 1511.87  4917.2 1504.10  4929.5 1501.30  4960.1 1498.47  4975.7 1498.61
  4993.2 1497.15  5014.1 1496.62  5014.4 1496.12  5018.2 1496.62  5032.3 1498.68
  5082.9 1503.06  5220.2 1509.22  5282.1 1513.13  5411.4 1523.19  5584.0 1533.19
  5634.6 1535.00  5701.6 1539.92  5732.3 1541.32  5740.8 1542.59  5775.1 1543.94
#Mann=6,-1,0
  4361.5   0.035       0  4446.7    0.07       0  4917.2   0.035       0
  5014.1   0.035       0  5018.2   0.035       0  5032.3    0.07       0
Bank Sta=5014.1,5018.2
Exp/Cntr=0.3,0.1

Type RM Length L Ch R = 1,6576,634,634,634
BEGIN DESCRIPTION:
Mapping XS 95a6c915
END DESCRIPTION:
XS GIS Cut Line= 3
      1658153.46      7017200.98      1658800.19      7016977.45
      1659503.99      7016702.42
#Sta/Elev= 30
  4309.6 1536.42  4382.0 1532.40  4428.7 1530.48  4589.4 1519.99  4642.3 1516.14
  4668.2 1511.90  4673.5 1512.36  4699.5 1507.55  4754.5 1504.25  4805.3 1501.56
  4924.9 1495.76  4991.7 1490.20  4991.9 1489.70  4995.9 1490.20  5089.4 1491.34
  5106.4 1494.11  5143.7 1495.16  5252.4 1502.36  5336.5 1506.17  5361.0 1509.86
  5390.8 1511.74  5415.3 1515.94  5420.7 1515.12  5445.1 1519.23  5529.3 1523.13
  5553.8 1527.29  5559.1 1526.52  5578.2 1529.08  5667.8 1533.52  5749.5 1540.17
#Mann=9,-1,0
  4309.6    0.07       0  4382.0   0.035       0  4428.7    0.07       0
  4589.4   0.035       0  4699.5    0.07       0  4754.5   0.035       0
  4805.3    0.07       0  4991.7    0.07       0  4995.9    0.07       0
Bank Sta=4991.7,4995.9
Exp/Cntr=0.3,0.1

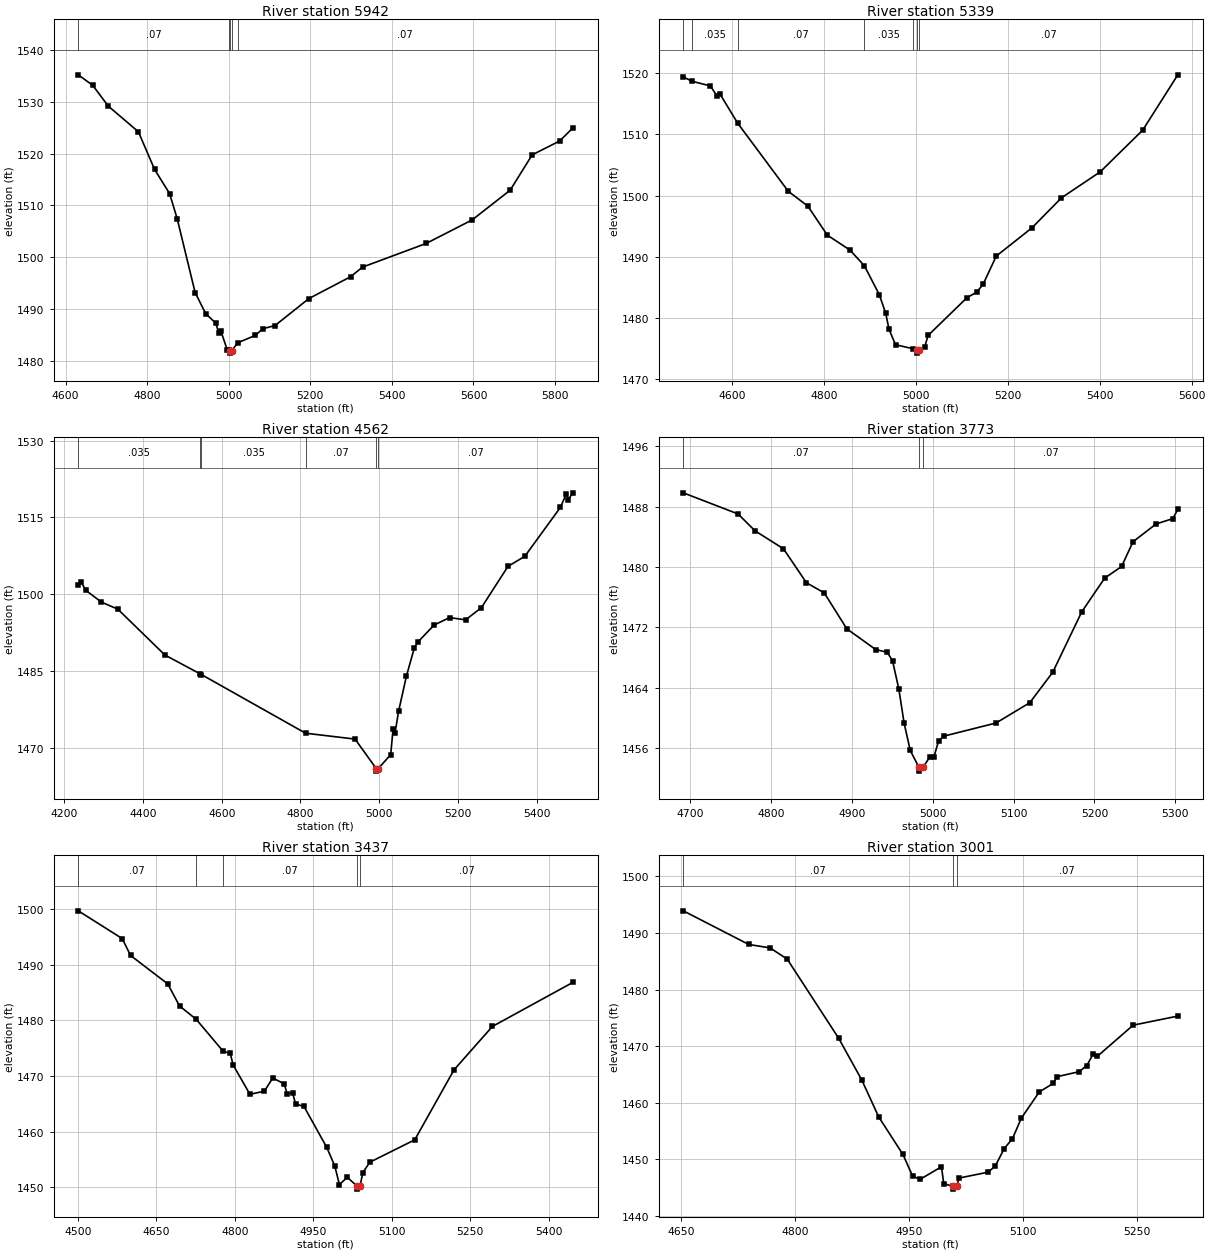
Type RM Length L Ch R = 1,5942,603,603,603
BEGIN DESCRIPTION:
Mapping XS b58af0fc
END DESCRIPTION:
XS GIS Cut Line= 3
      1658405.41      7017664.16      1658752.66      7017546.10
      1659537.37      7017230.13
#Sta/Elev= 30
  4630.9 1535.16  4666.5 1533.13  4704.4 1529.14  4778.3 1524.20  4818.1 1516.93
  4854.8 1512.30  4873.4 1507.47  4917.5 1493.22  4943.6 1489.14  4968.5 1487.31
  4975.0 1485.48  4980.3 1485.90  4996.3 1482.16  5000.3 1482.16  5003.6 1482.06
  5003.9 1481.56  5007.9 1482.06  5021.5 1483.54  5064.9 1484.97  5083.7 1486.27
  5113.2 1486.86  5196.5 1492.07  5298.6 1496.27  5328.1 1498.13  5483.9 1502.68
  5596.7 1507.21  5690.1 1512.94  5744.0 1519.75  5811.6 1522.42  5843.6 1524.92
#Mann=5,-1,0
  4630.9    0.07       0  5000.3   0.035       0  5003.6    0.07       0
  5007.9   0.035       0  5021.5    0.07       0
Bank Sta=5003.6,5007.9
Exp/Cntr=0.3,0.1

Type RM Length L Ch R = 1,5339,777,777,777
BEGIN DESCRIPTION:
Mapping XS 34d65aae
END DESCRIPTION:
XS GIS Cut Line= 3
      1658791.74      7018247.90      1659149.80      7017892.02
      1659537.32      7017472.02
#Sta/Elev= 30
  4493.6 1519.37  4512.2 1518.67  4552.4 1517.90  4566.6 1516.30  4573.6 1516.56
  4612.1 1511.80  4722.1 1500.70  4764.6 1498.29  4807.0 1493.55  4856.5 1491.10
  4887.9 1488.53  4920.1 1483.84  4934.3 1480.76  4941.3 1478.19  4955.5 1475.66
  4993.4 1475.01  5002.6 1474.79  5002.9 1474.29  5006.9 1474.79  5018.9 1475.24
  5026.3 1477.17  5111.3 1483.36  5132.3 1484.24  5146.5 1485.58  5174.8 1490.13
  5252.5 1494.74  5316.6 1499.63  5401.1 1503.88  5493.5 1510.68  5569.9 1519.71
#Mann=7,-1,0
  4493.6    0.07       0  4512.2   0.035       0  4612.1    0.07       0
  4887.9   0.035       0  4993.4    0.07       0  5002.6    0.07       0
  5006.9    0.07       0
Bank Sta=5002.6,5006.9
Exp/Cntr=0.3,0.1

Type RM Length L Ch R = 1,4562,789,789,789
BEGIN DESCRIPTION:
Mapping XS db3c2590
END DESCRIPTION:
XS GIS Cut Line= 3
      1658996.58      7018324.31      1659751.79      7018235.77
      1660246.55      7018201.91
#Sta/Elev= 30
  4235.6 1501.76  4242.9 1502.45  4254.1 1500.80  4294.4 1498.47  4336.2 1497.08
  4455.5 1488.14  4545.3 1484.44  4548.5 1484.31  4813.0 1472.85  4938.8 1471.70
  4992.6 1465.94  4993.0 1465.44  4997.6 1465.94  5029.3 1468.65  5035.4 1473.75
  5040.4 1472.92  5049.3 1477.12  5069.4 1484.05  5089.4 1489.53  5099.4 1490.75
  5139.5 1493.98  5178.8 1495.44  5219.7 1495.00  5259.8 1497.39  5327.2 1505.44
  5370.1 1507.42  5460.3 1516.96  5475.6 1519.63  5480.7 1518.51  5491.9 1519.82
#Mann=6,-1,0
  4235.6   0.035       0  4545.3    0.07       0  4548.5   0.035       0
  4813.0    0.07       0  4992.6    0.07       0  4997.6    0.07       0
Bank Sta=4992.6,4997.6
Exp/Cntr=0.3,0.1

Type RM Length L Ch R = 1,3773,336,336,336
BEGIN DESCRIPTION:
Mapping XS 8c7a0408
END DESCRIPTION:
XS GIS Cut Line= 3
      1659060.21      7018647.52      1659294.58      7018845.00
      1659521.21      7019050.04
#Sta/Elev= 30
  4691.1 1489.82  4758.9 1487.02  4779.8 1484.80  4815.1 1482.41  4843.5 1477.92
  4865.6 1476.57  4893.5 1471.82  4929.3 1469.07  4943.6 1468.71  4950.1 1467.59
  4957.9 1463.84  4964.4 1459.35  4972.0 1455.72  4982.8 1453.48  4983.1 1452.98
  4987.8 1453.48  4996.0 1454.81  5001.2 1454.81  5007.2 1457.02  5013.9 1457.62
  5078.2 1459.35  5120.0 1462.04  5148.4 1466.07  5184.3 1474.07  5212.7 1478.53
  5233.6 1480.07  5247.8 1483.35  5276.2 1485.69  5297.1 1486.41  5303.2 1487.64
#Mann=3,-1,0
  4691.1    0.07       0  4982.8    0.07       0  4987.8    0.07       0
Bank Sta=4982.8,4987.8
Exp/Cntr=0.3,0.1

Type RM Length L Ch R = 1,3437,436,436,436
BEGIN DESCRIPTION:
Mapping XS 1491f64e
END DESCRIPTION:
XS GIS Cut Line= 3
      1658820.07      7018648.40      1659060.83      7019085.70
      1659476.58      7019247.45
#Sta/Elev= 30
  4500.8 1499.71  4584.8 1494.72  4600.8 1491.68  4671.9 1486.56  4694.4 1482.59
  4726.2 1480.20  4777.8 1474.44  4791.2 1474.06  4797.1 1471.93  4829.0 1466.70
  4856.5 1467.27  4872.6 1469.64  4894.4 1468.59  4900.1 1466.81  4910.5 1466.99
  4916.2 1464.96  4932.2 1464.53  4975.8 1457.16  4991.2 1453.80  5000.0 1450.46
  5015.0 1451.79  5034.1 1450.15  5034.5 1449.65  5039.2 1450.15  5044.9 1452.64
  5058.1 1454.49  5144.0 1458.52  5219.1 1471.11  5292.4 1478.91  5446.1 1486.83
#Mann=5,-1,0
  4500.8    0.07       0  4726.2   0.035       0  4777.8    0.07       0
  5034.1    0.07       0  5039.2    0.07       0
Bank Sta=5034.1,5039.2
Exp/Cntr=0.3,0.1

Type RM Length L Ch R = 1,3001,410,410,410
BEGIN DESCRIPTION:
Mapping XS 7a4e5ef2
END DESCRIPTION:
XS GIS Cut Line= 3
      1658533.93      7019294.64      1658843.84      7019445.69
      1659125.13      7019565.50
#Sta/Elev= 30
  4652.8 1493.91  4738.9 1487.97  4767.0 1487.36  4789.5 1485.38  4857.1 1471.42
  4887.6 1464.03  4909.9 1457.50  4941.7 1450.89  4954.4 1447.08  4964.3 1446.49
  4992.4 1448.71  4995.4 1445.74  5007.1 1445.26  5007.5 1444.76  5012.2 1445.26
  5015.7 1446.72  5053.2 1447.74  5062.9 1448.76  5074.9 1451.91  5085.8 1453.67
  5097.4 1457.28  5121.1 1461.93  5139.3 1463.42  5144.7 1464.62  5173.7 1465.51
  5183.6 1466.59  5191.9 1468.60  5197.4 1468.21  5244.6 1473.72  5303.3 1475.32
#Mann=3,-1,0
  4652.8    0.07       0  5007.1    0.07       0  5012.2    0.07       0
Bank Sta=5007.1,5012.2
Exp/Cntr=0.3,0.1

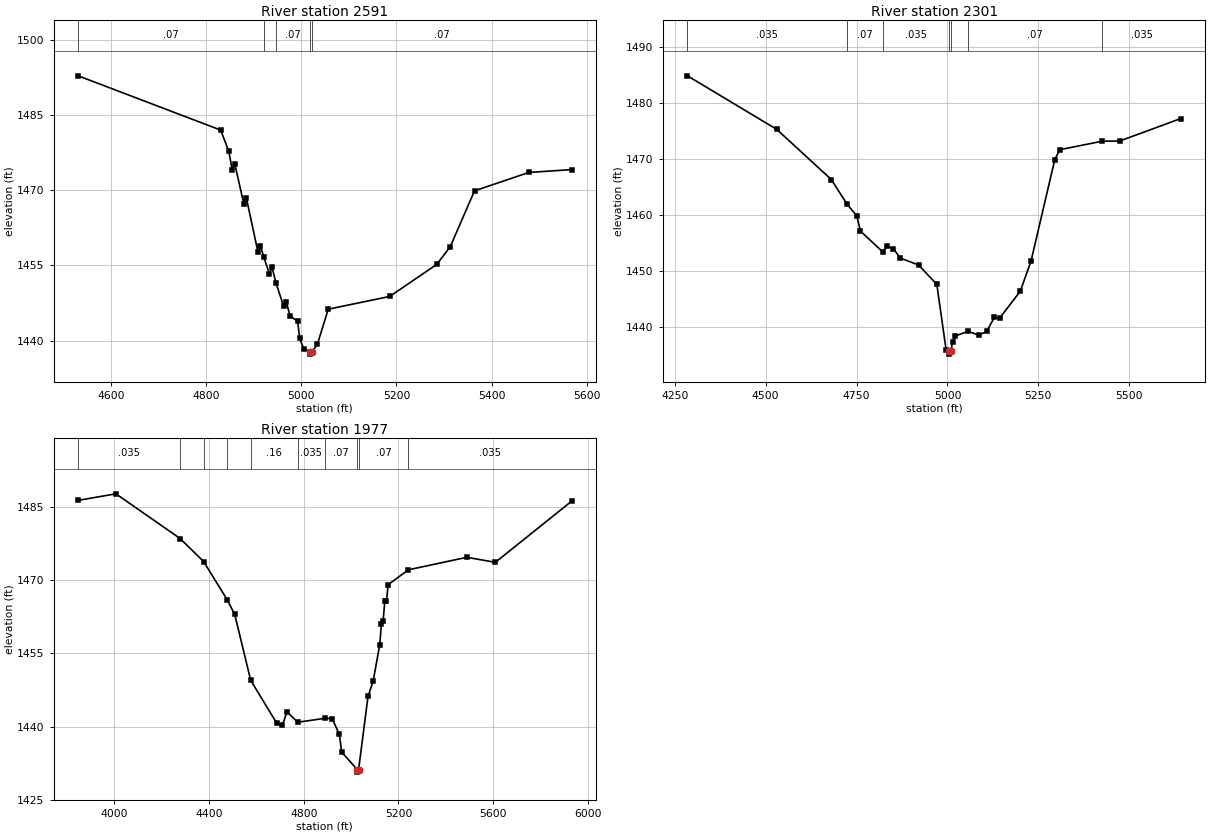
Type RM Length L Ch R = 1,2591,290,290,290
BEGIN DESCRIPTION:
Mapping XS f335fb53
END DESCRIPTION:
XS GIS Cut Line= 3
      1658320.77      7019652.53      1658756.92      7019826.05
      1659271.21      7019584.71
#Sta/Elev= 30
  4530.6 1492.84  4830.3 1482.01  4847.3 1477.77  4854.6 1474.06  4859.9 1475.27
  4878.9 1467.28  4884.2 1468.51  4908.5 1457.73  4913.9 1458.89  4921.1 1456.61
  4932.8 1453.33  4938.2 1454.65  4946.8 1451.43  4962.5 1446.90  4967.9 1447.77
  4976.4 1444.89  4992.1 1443.86  4996.3 1440.47  5005.3 1438.27  5017.4 1437.80
  5017.8 1437.30  5022.6 1437.80  5033.6 1439.26  5056.5 1446.27  5185.7 1448.81
  5284.6 1455.20  5313.0 1458.73  5364.1 1469.89  5478.2 1473.55  5568.1 1474.13
#Mann=5,-1,0
  4530.6    0.07       0  4921.1   0.035       0  4946.8    0.07       0
  5017.4    0.07       0  5022.6    0.07       0
Bank Sta=5017.4,5022.6
Exp/Cntr=0.3,0.1

Type RM Length L Ch R = 1,2301,324,324,324
BEGIN DESCRIPTION:
Mapping XS 382de064
END DESCRIPTION:
XS GIS Cut Line= 3
      1658199.40      7020067.64      1658911.16      7020048.56
      1659436.37      7019674.86
#Sta/Elev= 30
  4285.0 1484.90  4530.7 1475.31  4680.7 1466.33  4723.0 1462.00  4750.8 1459.81
  4760.8 1457.10  4822.1 1453.38  4833.5 1454.38  4850.8 1453.97  4870.8 1452.27
  4920.8 1451.02  4970.8 1447.56  4996.4 1435.80  5004.6 1435.58  5005.0 1435.08
  5009.8 1435.58  5014.0 1437.30  5022.0 1438.35  5057.0 1439.15  5087.2 1438.46
  5108.1 1439.19  5129.0 1441.65  5143.7 1441.53  5200.3 1446.35  5229.8 1451.72
  5295.0 1469.85  5308.5 1471.67  5425.9 1473.20  5473.3 1473.22  5641.6 1477.25
#Mann=7,-1,0
  4285.0   0.035       0  4723.0    0.07       0  4822.1   0.035       0
  5004.6   0.035       0  5009.8   0.035       0  5057.0    0.07       0
  5425.9   0.035       0
Bank Sta=5004.6,5009.8
Exp/Cntr=0.3,0.1

Type RM Length L Ch R = 1,1977,0,0,0
BEGIN DESCRIPTION:
Chimney Creek 1173 3.0
END DESCRIPTION:
XS GIS Cut Line= 3
      1658006.31      7020154.45      1659154.46      7020248.63
      1659805.34      7019583.67
#Sta/Elev= 30
  3848.0 1486.35  4007.2 1487.68  4278.5 1478.52  4377.7 1473.79  4476.9 1465.99
  4508.9 1462.97  4576.0 1449.50  4685.5 1440.75  4709.6 1440.24  4729.6 1443.04
  4774.3 1440.90  4889.7 1441.70  4920.3 1441.63  4950.4 1438.41  4960.4 1434.78
  5026.4 1431.18  5026.8 1430.68  5031.6 1431.18  5071.5 1446.22  5092.8 1449.25
  5121.1 1456.80  5128.1 1461.12  5135.2 1461.57  5142.2 1465.65  5149.4 1465.63
  5156.3 1469.07  5242.0 1472.12  5488.8 1474.68  5609.0 1473.65  5930.5 1486.15
#Mann=10,-1,0
  3848.0   0.035       0  4278.5    0.07       0  4377.7   0.035       0
  4476.9    0.07       0  4576.0    0.16       0  4774.3   0.035       0
  4889.7    0.07       0  5026.4    0.07       0  5031.6    0.07       0
  5242.0   0.035       0
Bank Sta=5026.4,5031.6
Exp/Cntr=0.3,0.1

Chan Stop Cuts=-1