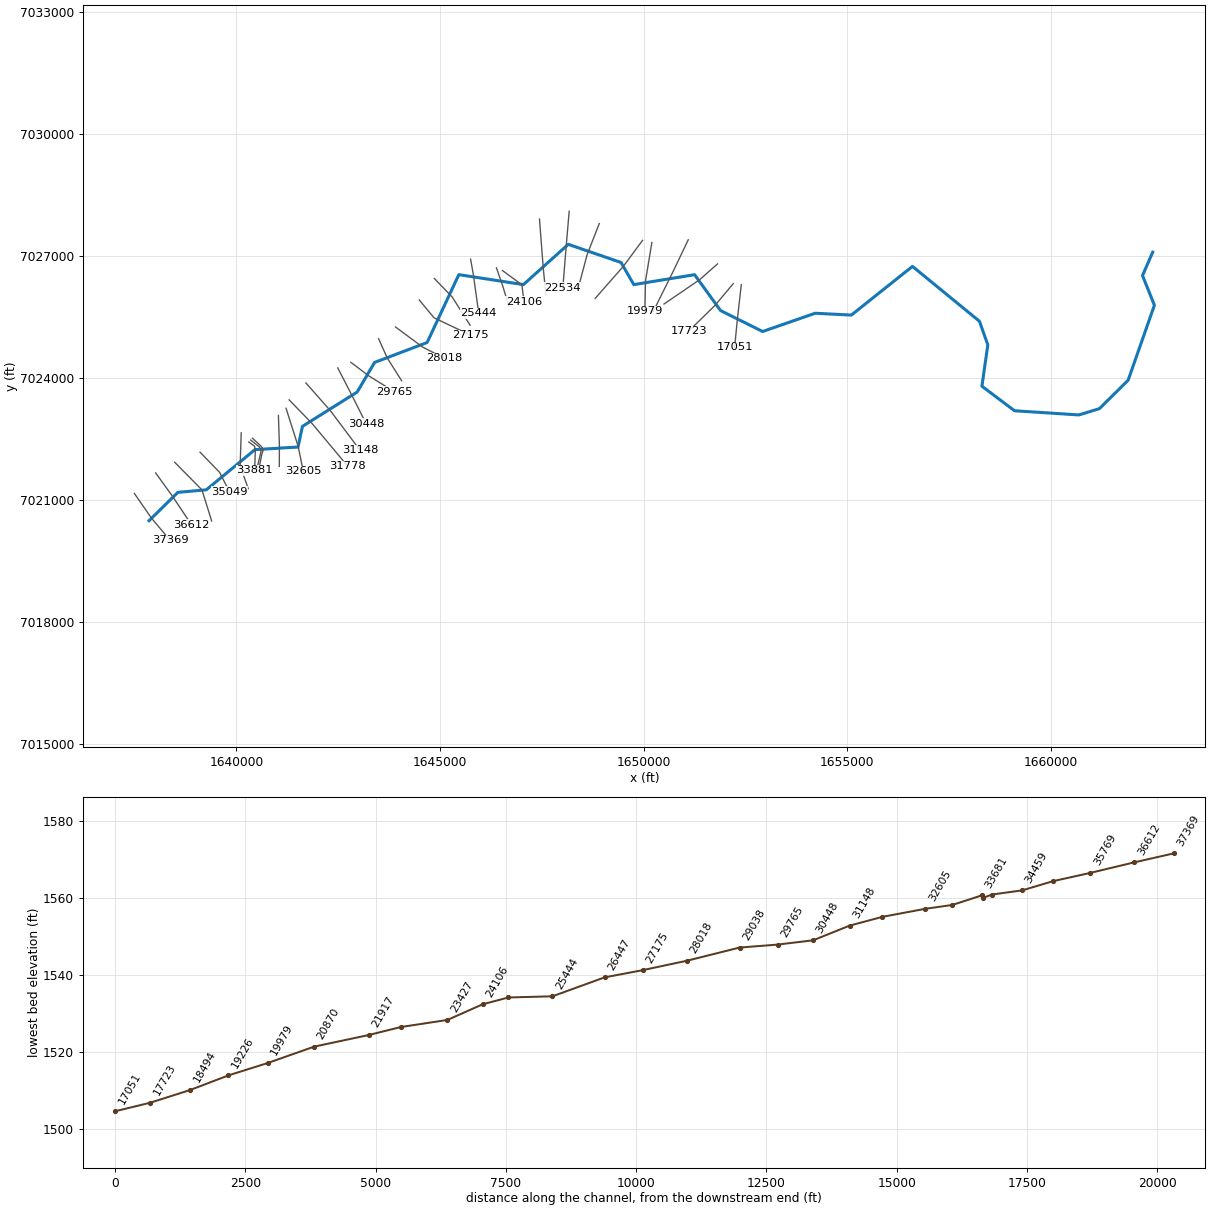
--- Chimney Creek 1174.prj (project) ---

Proj Title=Chimney Creek 1174 Base Level Engineering
Current Plan=p01
Default Exp/Contr=0.3,0.1
English Units
Geom File=g01
Flow File=f01
Plan File=p01
BEGIN DESCRIPTION:
Chimney Creek 1174
END DESCRIPTION:

--- Chimney Creek 1174.p01 (plan) ---

Plan Title=Multiple Run
Short Identifier=Multiple
Geom File=g01
Flow File=f01
Subcritical Flow
K Sum by GR= 0
Std Step Tol= 0.01
Critical Tol= 0.01
Num of Std Step Trials= 20
Max Error Tol= 0.3
Flow Tol Ratio= 0.001
Split Flow NTrial= 30
Split Flow Tol= 0.02
Split Flow Ratio= 0.02
Log Output Level= 0
Friction Slope Method= 1
Unsteady Friction Slope Method= 2
Unsteady Bridges Friction Slope Method= 1
Parabolic Critical Depth
Global Vel Dist=  1 , 1 , 1
Global Log Level= 0
CheckData=True
Encroach Param= -1, 0, 0, 0
BEGIN DESCRIPTION:
Multiple Run
END DESCRIPTION:

--- Chimney Creek 1174.f01 (steady flow) ---

Flow Title=Multiple
Number of Profiles=7
Profile Names=10-year,25-year,50-year,1pct_min,100-year,1pct_plu,500-year
River Rch & RM= Chimney Creek 11,Reach-1,37369
     255     348     423     256     511    1019     755
River Rch & RM= Chimney Creek 11,Reach-1,33881
     342     473     582     355     709    1414    1066
River Rch & RM= Chimney Creek 11,Reach-1,31148
     420     587     726     446     889    1774    1353
River Rch & RM= Chimney Creek 11,Reach-1,29765
     475     669     832     513    1023    2042    1571
River Rch & RM= Chimney Creek 11,Reach-1,28018
     540     764     953     589    1176    2346    1816
River Rch & RM= Chimney Creek 11,Reach-1,23427
     737    1057    1328     828    1652    3296    2590
River Rch & RM= Chimney Creek 11,Reach-1,17051
     753    1081    1359     847    1691    3374    2653
River Rch & RM= Chimney Creek 11,Reach-1,15160
     967    1403    1778    1117    2228    4445    3546
River Rch & RM= Chimney Creek 11,Reach-1,11945
    1161    1701    2171    1372    2738    5464    4416
Boundary for River Rch & Prof#=Chimney Creek 11,Reach-1,1
Up Type=0
Dn Type=3
Dn Slope=0.005
Boundary for River Rch & Prof#=Chimney Creek 11,Reach-1,2
Up Type=0
Dn Type=3
Dn Slope=0.005
Boundary for River Rch & Prof#=Chimney Creek 11,Reach-1,3
Up Type=0
Dn Type=3
Dn Slope=0.005
Boundary for River Rch & Prof#=Chimney Creek 11,Reach-1,4
Up Type=0
Dn Type=3
Dn Slope=0.005
Boundary for River Rch & Prof#=Chimney Creek 11,Reach-1,5
Up Type=0
Dn Type=3
Dn Slope=0.005
Boundary for River Rch & Prof#=Chimney Creek 11,Reach-1,6
Up Type=0
Dn Type=3
Dn Slope=0.005
Boundary for River Rch & Prof#=Chimney Creek 11,Reach-1,7
Up Type=0
Dn Type=3
Dn Slope=0.005

--- Chimney Creek 1174.g01 (geometry) ---

Geom Title=Existing Conditions

River Reach=Chimney Creek 11,Reach-1
Reach XY= 30
      1637855.00      7020488.00      1638563.64      7021185.00
      1639261.95      7021247.18      1640456.65      7022234.90
      1641515.18      7022298.32      1641621.46      7022805.14
      1642968.32      7023651.37      1643394.88      7024377.65
      1644685.27      7024867.57      1645463.28      7026534.94
      1647049.08      7026290.23      1648151.70      7027279.92
      1649446.54      7026834.50      1649760.93      7026290.23
      1651253.54      7026534.46      1651891.79      7025651.63
      1652925.06      7025137.79      1654214.65      7025586.64
      1655103.44      7025541.74      1656605.00      7026738.00
      1658249.15      7025390.29      1658455.29      7024810.84
      1658310.62      7023793.62      1659110.93      7023190.25
      1660691.18      7023087.56      1661196.38      7023241.84
      1661901.39      7023939.50      1662546.92      7025784.70
      1662254.68      7026512.89      1662505.00      7027088.00

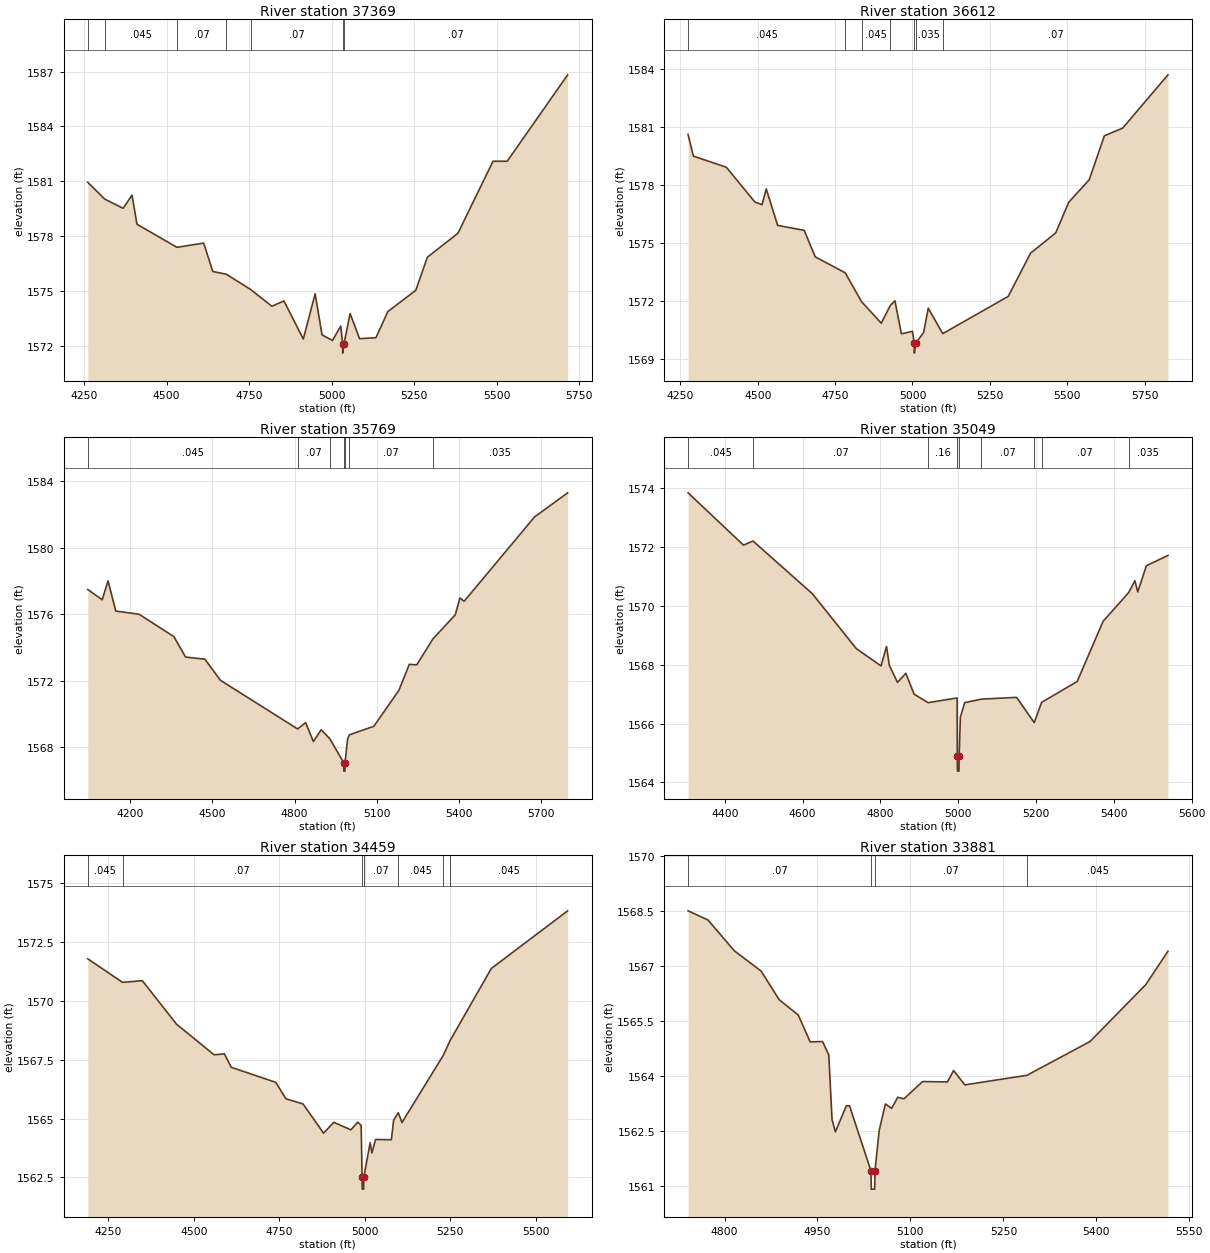
Type RM Length L Ch R = 1,37369,757,757,757
BEGIN DESCRIPTION:
Chimney Creek 1174 76.0
END DESCRIPTION:
XS GIS Cut Line= 3
      1637496.25      7021156.97      1637916.36      7020549.36
      1638377.26      7020001.83
#Sta/Elev= 30
  4261.3 1580.95  4312.9 1580.03  4368.4 1579.53  4395.4 1580.25  4410.3 1578.66
  4531.5 1577.40  4612.6 1577.63  4640.1 1576.08  4681.0 1575.93  4754.6 1575.10
  4819.3 1574.18  4855.8 1574.47  4914.5 1572.39  4950.3 1574.86  4971.2 1572.62
  5002.8 1572.31  5027.9 1573.10  5033.6 1572.12  5033.8 1571.62  5037.6 1572.12
  5056.4 1573.78  5085.0 1572.41  5134.5 1572.46  5170.8 1573.89  5255.4 1575.05
  5290.5 1576.86  5382.9 1578.16  5489.5 1582.10  5532.4 1582.10  5715.7 1586.82
#Mann=7,-1,0
  4261.3   0.035       0  4312.9   0.045       0  4531.5    0.07       0
  4681.0   0.045       0  4754.6    0.07       0  5033.6    0.07       0
  5037.6    0.07       0
Bank Sta=5033.6,5037.6
Exp/Cntr=0.3,0.1

Type RM Length L Ch R = 1,36612,843,843,843
BEGIN DESCRIPTION:
Mapping XS 26589a84
END DESCRIPTION:
XS GIS Cut Line= 3
      1638017.13      7021662.83      1638433.77      7021085.62
      1638898.18      7020386.84
#Sta/Elev= 30
  4274.9 1580.62  4292.0 1579.50  4398.7 1578.92  4490.8 1577.12  4514.0 1576.98
  4527.5 1577.80  4564.3 1575.91  4650.2 1575.65  4685.8 1574.28  4782.8 1573.45
  4835.8 1571.95  4899.3 1570.84  4928.1 1571.75  4943.4 1572.00  4964.3 1570.29
  5000.0 1570.42  5005.8 1569.79  5006.1 1569.29  5010.0 1569.79  5036.1 1570.36
  5051.1 1571.62  5097.9 1570.30  5309.6 1572.23  5381.8 1574.47  5463.0 1575.52
  5505.1 1577.11  5571.2 1578.27  5620.3 1580.55  5679.4 1580.95  5825.8 1583.71
#Mann=7,-1,0
  4274.9   0.045       0  4782.8   0.035       0  4835.8   0.045       0
  4928.1   0.035       0  5005.8   0.035       0  5010.0   0.035       0
  5097.9    0.07       0
Bank Sta=5005.8,5010
Exp/Cntr=0.3,0.1

Type RM Length L Ch R = 1,35769,720,720,720
BEGIN DESCRIPTION:
Mapping XS b1891f7a
END DESCRIPTION:
XS GIS Cut Line= 3
      1638485.83      7021923.32      1639154.26      7021246.21
      1639392.86      7020482.68
#Sta/Elev= 30
  4045.5 1577.49  4098.1 1576.87  4119.4 1578.01  4147.7 1576.19  4232.6 1576.00
  4359.8 1574.65  4402.3 1573.42  4473.0 1573.29  4529.6 1572.02  4811.3 1569.09
  4840.6 1569.47  4868.9 1568.33  4897.2 1569.04  4928.4 1568.51  4979.8 1567.05
  4980.1 1566.55  4984.0 1566.55  4984.3 1567.05  4993.9 1568.51  5000.6 1568.74
  5089.4 1569.25  5181.1 1571.42  5218.9 1572.98  5246.1 1572.95  5305.0 1574.51
  5386.5 1575.96  5403.7 1576.98  5419.0 1576.78  5676.1 1581.86  5796.9 1583.31
#Mann=7,-1,0
  4045.5   0.045       0  4811.3    0.07       0  4928.4    0.16       0
  4979.8    0.07       0  4984.3    0.16       0  5000.6    0.07       0
  5305.0   0.035       0
Bank Sta=4979.8,4984.3
Exp/Cntr=0.3,0.1

Type RM Length L Ch R = 1,35049,590,590,590
BEGIN DESCRIPTION:
Mapping XS 62676bc2
END DESCRIPTION:
XS GIS Cut Line= 3
      1639107.91      7022172.36      1639587.48      7021677.60
      1639834.47      7021192.27
#Sta/Elev= 30
  4305.5 1573.85  4448.0 1572.07  4472.4 1572.21  4624.8 1570.42  4737.9 1568.55
  4801.5 1567.96  4815.6 1568.62  4822.8 1567.98  4843.9 1567.40  4865.3 1567.71
  4886.4 1567.00  4922.5 1566.71  4997.1 1566.87  4997.5 1564.88  4997.9 1564.38
  5001.9 1564.38  5002.2 1564.88  5005.5 1566.22  5016.5 1566.71  5059.6 1566.83
  5150.0 1566.89  5195.3 1566.03  5214.3 1566.72  5305.7 1567.43  5372.4 1569.48
  5437.8 1570.45  5454.1 1570.86  5461.4 1570.48  5483.7 1571.37  5539.1 1571.72
#Mann=9,-1,0
  4305.5   0.045       0  4472.4    0.07       0  4922.5    0.16       0
  4997.5    0.07       0  5002.2    0.16       0  5059.6    0.07       0
  5195.3    0.16       0  5214.3    0.07       0  5437.8   0.035       0
Bank Sta=4997.5,5002.2
Exp/Cntr=0.3,0.1

Type RM Length L Ch R = 1,34459,578,578,578
BEGIN DESCRIPTION:
Mapping XS dd64cfe8
END DESCRIPTION:
XS GIS Cut Line= 3
      1640119.16      7022647.62      1640093.12      7021842.53
      1640290.29      7021277.03
#Sta/Elev= 30
  4189.6 1571.79  4291.2 1570.79  4349.3 1570.86  4449.4 1569.01  4559.4 1567.71
  4589.4 1567.75  4609.4 1567.18  4739.5 1566.54  4769.5 1565.84  4819.6 1565.62
  4879.6 1564.38  4909.6 1564.84  4959.6 1564.52  4979.6 1564.85  4989.6 1564.71
  4992.4 1562.50  4992.8 1562.00  4997.0 1562.00  4997.3 1562.50  5015.9 1563.97
  5021.2 1563.54  5031.7 1564.11  5078.0 1564.10  5084.6 1564.93  5098.2 1565.25
  5109.1 1564.83  5230.1 1567.69  5250.5 1568.33  5370.6 1571.38  5594.0 1573.83
#Mann=7,-1,0
  4189.6   0.045       0  4291.2    0.07       0  4992.4    0.07       0
  4997.3    0.07       0  5098.2   0.045       0  5230.1    0.07       0
  5250.5   0.045       0
Bank Sta=4992.4,4997.3
Exp/Cntr=0.3,0.1

Type RM Length L Ch R = 1,33881,164,164,164
BEGIN DESCRIPTION:
Mapping XS 64dee268
END DESCRIPTION:
XS GIS Cut Line= 4
      1640304.98      7022422.84      1640445.61      7022318.67
      1640466.45      7022238.81      1640449.11      7021722.25
#Sta/Elev= 30
  4741.2 1568.50  4773.4 1568.25  4815.9 1567.41  4859.0 1566.86  4888.2 1566.08
  4919.1 1565.66  4938.2 1564.93  4958.2 1564.94  4968.3 1564.57  4973.5 1562.82
  4978.9 1562.48  4996.6 1563.19  5001.7 1563.19  5036.3 1561.42  5036.8 1560.92
  5042.3 1560.92  5042.8 1561.42  5049.6 1562.52  5059.6 1563.24  5069.6 1563.12
  5079.6 1563.42  5089.6 1563.38  5119.6 1563.85  5159.6 1563.84  5169.7 1564.15
  5187.8 1563.76  5288.0 1564.02  5389.8 1564.94  5479.8 1566.49  5515.6 1567.40
#Mann=4,-1,0
  4741.2    0.07       0  5036.3    0.07       0  5042.8    0.07       0
  5288.0   0.045       0
Bank Sta=5036.3,5042.8
Exp/Cntr=0.3,0.1

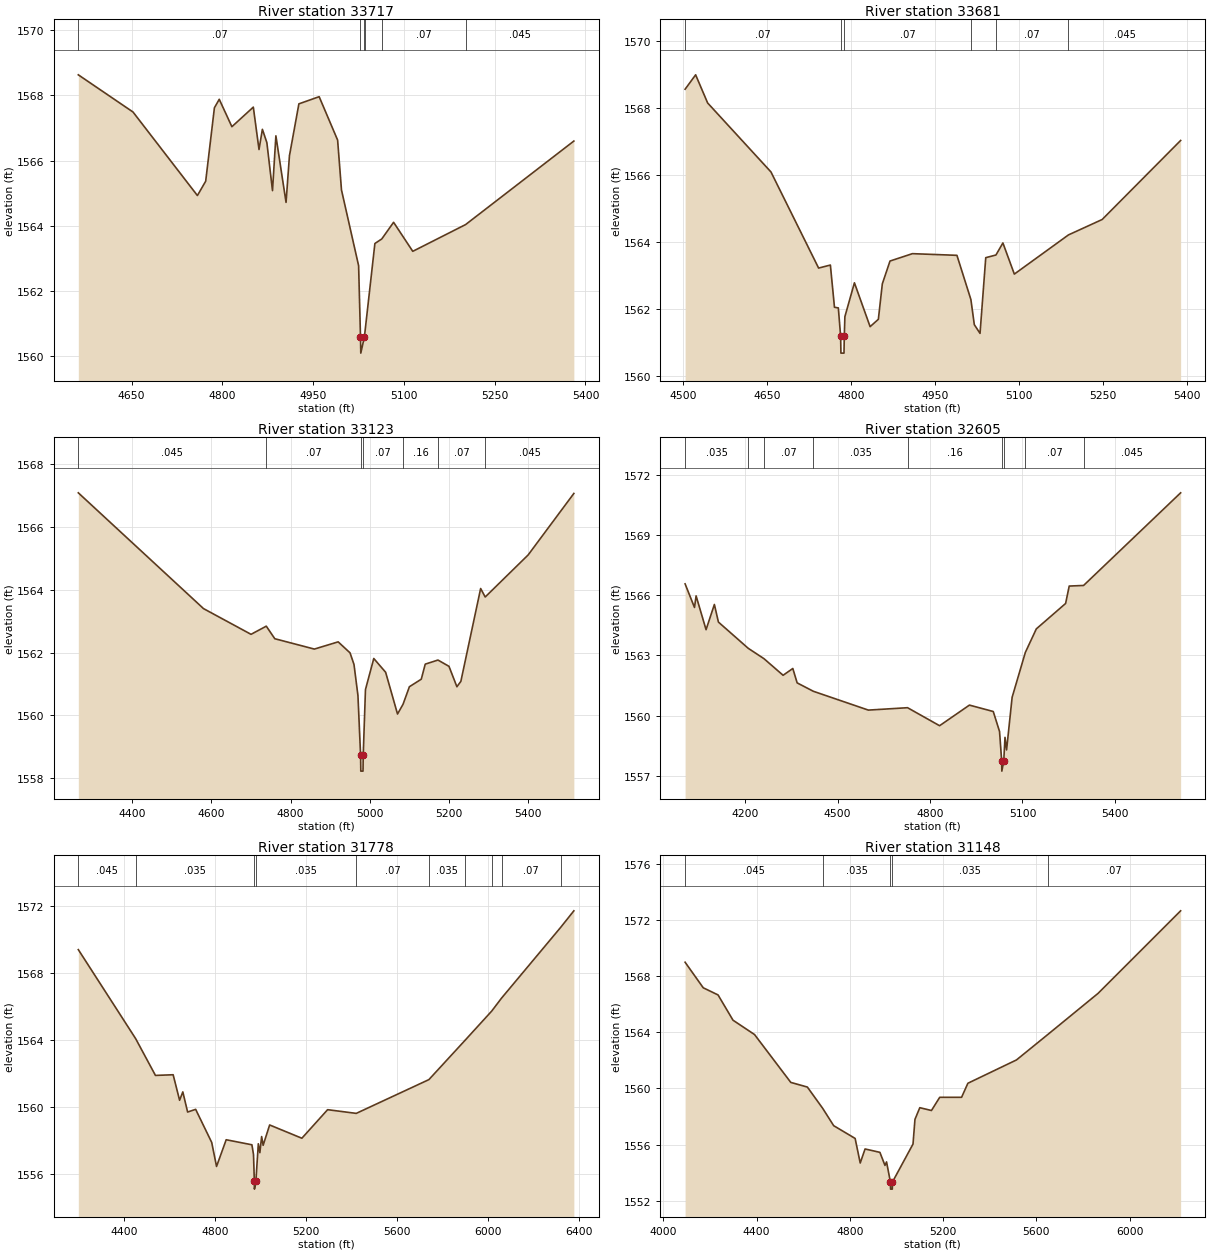
Type RM Length L Ch R = 1,33717,36,36,36
BEGIN DESCRIPTION:
Mapping XS adde1227
END DESCRIPTION:
XS GIS Cut Line= 5
      1640351.15      7022470.86      1640569.94      7022296.35
      1640609.00      7022218.23      1640595.98      7022150.52
      1640507.45      7021778.15
#Sta/Elev= 30
  4561.9 1568.63  4652.3 1567.49  4758.7 1564.93  4772.4 1565.37  4786.8 1567.62
  4794.8 1567.88  4815.7 1567.04  4851.1 1567.64  4860.5 1566.34  4866.1 1566.96
  4873.5 1566.55  4882.8 1565.08  4888.4 1566.76  4905.2 1564.72  4910.8 1566.15
  4926.4 1567.74  4959.9 1567.96  4990.4 1566.63  4996.8 1565.10  5025.1 1562.78
  5028.2 1560.60  5028.7 1560.10  5034.7 1560.60  5035.0 1560.65  5052.0 1563.46
  5063.4 1563.60  5082.9 1564.11  5114.6 1563.22  5201.9 1564.04  5380.8 1566.60
#Mann=6,-1,0
  4561.9    0.07       0  5028.2    0.07       0  5034.7    0.07       0
  5035.0    0.16       0  5063.4    0.07       0  5201.9   0.045       0
Bank Sta=5028.2,5034.7
Exp/Cntr=0.3,0.1

Type RM Length L Ch R = 1,33681,558,558,558
BEGIN DESCRIPTION:
Mapping XS e292e2a7
END DESCRIPTION:
XS GIS Cut Line= 5
      1640395.49      7022515.08      1640606.40      7022319.79
      1640666.30      7022239.06      1640629.84      7022140.10
      1640551.72      7021757.31
#Sta/Elev= 30
  4504.3 1568.56  4523.1 1568.99  4544.5 1568.15  4657.5 1566.09  4742.5 1563.22
  4763.5 1563.31  4770.8 1562.05  4777.7 1562.03  4781.8 1561.18  4782.3 1560.68
  4787.8 1560.68  4788.3 1561.18  4789.4 1561.77  4806.4 1562.78  4834.4 1561.47
  4849.1 1561.69  4856.2 1562.75  4869.9 1563.43  4909.9 1563.65  4989.3 1563.60
  5014.2 1562.28  5020.3 1561.53  5030.5 1561.27  5040.7 1563.53  5058.9 1563.61
  5071.3 1563.97  5091.7 1563.04  5188.3 1564.21  5248.4 1564.67  5388.4 1567.03
#Mann=6,-1,0
  4504.3    0.07       0  4781.8    0.07       0  4788.3    0.07       0
  5014.2    0.16       0  5058.9    0.07       0  5188.3   0.045       0
Bank Sta=4781.8,4788.3
Exp/Cntr=0.3,0.1

Type RM Length L Ch R = 1,33123,518,518,518
BEGIN DESCRIPTION:
Mapping XS 66681001
END DESCRIPTION:
XS GIS Cut Line= 3
      1641033.05      7023074.12      1641056.92      7022344.96
      1641054.75      7021822.51
#Sta/Elev= 30
  4263.6 1567.09  4579.9 1563.40  4700.0 1562.58  4738.5 1562.84  4760.0 1562.44
  4860.0 1562.11  4920.1 1562.34  4950.1 1561.99  4960.1 1561.62  4970.1 1560.63
  4976.8 1558.72  4977.3 1558.22  4982.9 1558.22  4983.4 1558.72  4989.1 1560.82
  5010.1 1561.81  5040.1 1561.37  5070.1 1560.04  5084.0 1560.35  5100.1 1560.91
  5130.1 1561.15  5140.1 1561.63  5172.3 1561.76  5200.1 1561.56  5220.1 1560.91
  5230.1 1561.08  5280.1 1564.04  5291.6 1563.77  5400.1 1565.11  5515.6 1567.07
#Mann=7,-1,0
  4263.6   0.045       0  4738.5    0.07       0  4976.8    0.07       0
  4983.4    0.07       0  5084.0    0.16       0  5172.3    0.07       0
  5291.6   0.045       0
Bank Sta=4976.8,4983.4
Exp/Cntr=0.3,0.1

Type RM Length L Ch R = 1,32605,827,827,827
BEGIN DESCRIPTION:
Mapping XS 443d00c3
END DESCRIPTION:
XS GIS Cut Line= 3
      1641220.43      7023251.00      1641519.92      7022308.26
      1641642.17      7021702.23
#Sta/Elev= 30
  4005.6 1566.58  4036.1 1565.40  4041.3 1565.98  4073.6 1564.29  4100.6 1565.55
  4113.7 1564.67  4210.3 1563.36  4261.5 1562.84  4323.5 1562.01  4355.0 1562.35
  4369.1 1561.63  4421.8 1561.21  4600.1 1560.27  4727.2 1560.39  4831.1 1559.49
  4927.9 1560.52  5005.2 1560.20  5025.6 1559.20  5032.5 1557.72  5033.0 1557.22
  5039.2 1557.72  5043.3 1558.91  5048.4 1558.28  5066.4 1560.91  5109.2 1563.15
  5144.9 1564.33  5239.9 1565.60  5251.6 1566.47  5298.2 1566.50  5613.0 1571.13
#Mann=9,-1,0
  4005.6   0.035       0  4210.3   0.045       0  4261.5    0.07       0
  4421.8   0.035       0  4727.2    0.16       0  5032.5    0.07       0
  5039.2    0.16       0  5109.2    0.07       0  5298.2   0.045       0
Bank Sta=5032.5,5039.2
Exp/Cntr=0.3,0.1

Type RM Length L Ch R = 1,31778,630,630,630
BEGIN DESCRIPTION:
Mapping XS 9ccfafa3
END DESCRIPTION:
XS GIS Cut Line= 3
      1641295.19      7023458.19      1641849.89      7022887.87
      1642737.90      7021825.39
#Sta/Elev= 30
  4197.9 1569.38  4450.2 1564.08  4537.3 1561.89  4615.2 1561.93  4643.5 1560.41
  4657.7 1560.91  4678.8 1559.71  4714.2 1559.87  4784.8 1557.90  4806.1 1556.47
  4848.5 1558.06  4961.7 1557.76  4968.7 1557.18  4972.3 1555.62  4972.8 1555.12
  4979.3 1555.62  4989.9 1557.82  4996.7 1557.29  5004.5 1558.25  5011.1 1557.73
  5039.7 1558.94  5181.5 1558.15  5294.8 1559.85  5420.8 1559.63  5740.4 1561.64
  5900.1 1563.99  6016.7 1565.72  6059.9 1566.49  6319.9 1570.70  6378.2 1571.69
#Mann=10,-1,0
  4197.9   0.045       0  4450.2   0.035       0  4972.3   0.035       0
  4979.3   0.035       0  5420.8    0.07       0  5740.4   0.035       0
  5900.1    0.07       0  6016.7   0.035       0  6059.9    0.07       0
  6319.9   0.035       0
Bank Sta=4972.3,4979.3
Exp/Cntr=0.3,0.1

Type RM Length L Ch R = 1,31148,700,700,700
BEGIN DESCRIPTION:
Mapping XS ed770eec
END DESCRIPTION:
XS GIS Cut Line= 3
      1641709.29      7023872.22      1642308.22      7023192.56
      1643039.98      7022216.01
#Sta/Elev= 30
  4093.1 1568.99  4170.9 1567.17  4234.5 1566.66  4298.7 1564.86  4391.0 1563.84
  4546.6 1560.43  4617.7 1560.10  4683.6 1558.58  4730.6 1557.35  4822.7 1556.44
  4844.5 1554.69  4865.3 1555.69  4928.9 1555.45  4950.7 1554.52  4957.4 1554.77
  4974.2 1553.33  4974.7 1552.83  4982.1 1552.83  4982.6 1553.33  5071.0 1556.04
  5079.4 1557.80  5100.2 1558.63  5150.2 1558.43  5185.6 1559.37  5279.4 1559.37
  5306.5 1560.37  5514.9 1562.03  5648.5 1563.83  5864.9 1566.77  6219.3 1572.65
#Mann=5,-1,0
  4093.1   0.045       0  4683.6   0.035       0  4974.2   0.035       0
  4982.6   0.035       0  5648.5    0.07       0
Bank Sta=4974.2,4982.6
Exp/Cntr=0.3,0.1

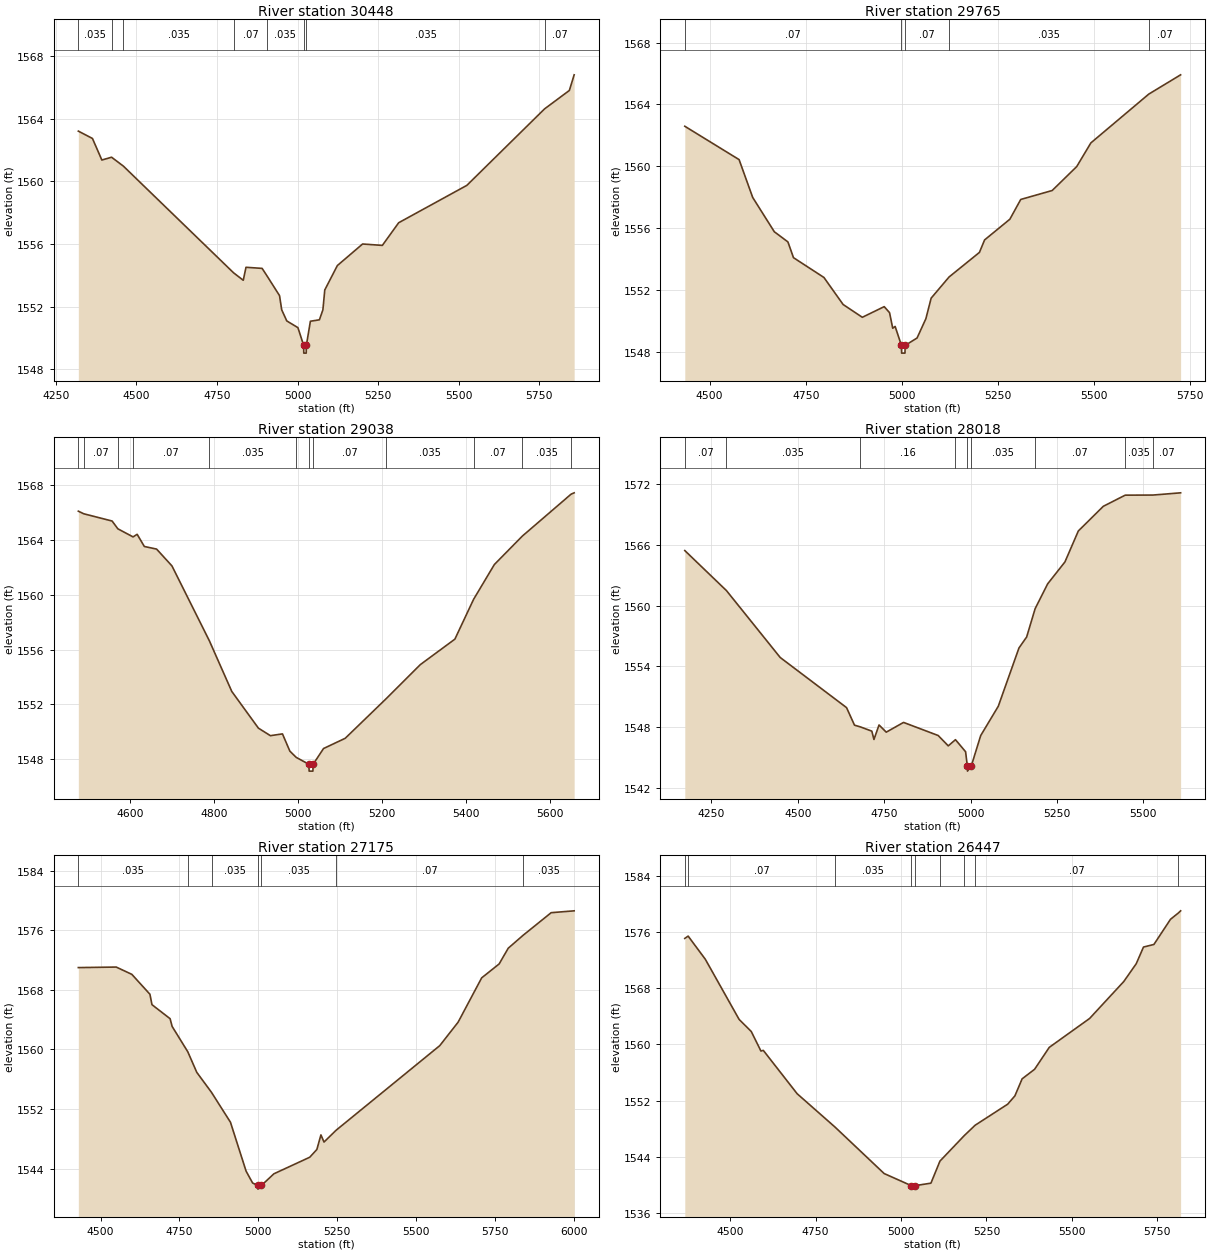
Type RM Length L Ch R = 1,30448,683,683,683
BEGIN DESCRIPTION:
Mapping XS e217fc97
END DESCRIPTION:
XS GIS Cut Line= 3
      1642490.44      7024242.88      1642800.32      7023641.34
      1643187.74      7022871.71
#Sta/Elev= 30
  4319.7 1563.22  4363.5 1562.75  4392.7 1561.37  4422.8 1561.55  4459.5 1560.98
  4801.2 1554.16  4831.4 1553.68  4839.9 1554.51  4889.9 1554.44  4905.7 1553.94
  4943.9 1552.70  4950.7 1551.79  4966.4 1551.08  5001.0 1550.65  5018.7 1549.52
  5019.2 1549.02  5026.7 1549.02  5027.2 1549.52  5039.7 1551.06  5067.6 1551.15
  5078.5 1551.79  5084.3 1553.06  5123.3 1554.62  5201.6 1556.00  5262.9 1555.91
  5313.6 1557.36  5525.1 1559.75  5766.1 1564.64  5843.1 1565.82  5858.0 1566.82
#Mann=8,-1,0
  4319.7   0.035       0  4422.8    0.07       0  4459.5   0.035       0
  4801.2    0.07       0  4905.7   0.035       0  5018.7   0.035       0
  5027.2   0.035       0  5766.1    0.07       0
Bank Sta=5018.7,5027.2
Exp/Cntr=0.3,0.1

Type RM Length L Ch R = 1,29765,727,727,727
BEGIN DESCRIPTION:
Mapping XS 59d28831
END DESCRIPTION:
XS GIS Cut Line= 3
      1642811.28      7024381.08      1643259.18      7024042.56
      1643879.00      7023660.59
#Sta/Elev= 30
  4435.4 1562.59  4576.6 1560.43  4612.0 1557.98  4668.2 1555.76  4703.6 1555.10
  4718.1 1554.08  4797.2 1552.80  4847.1 1551.05  4897.1 1550.22  4954.0 1550.91
  4967.9 1550.52  4976.2 1549.51  4982.4 1549.63  4998.8 1548.40  4999.3 1547.90
  5008.0 1547.90  5008.5 1548.40  5039.5 1548.88  5062.4 1550.13  5076.1 1551.46
  5122.7 1552.83  5201.6 1554.42  5215.1 1555.23  5280.8 1556.57  5309.1 1557.85
  5390.9 1558.43  5454.7 1559.98  5491.4 1561.51  5642.0 1564.67  5724.9 1565.92
#Mann=5,-1,0
  4435.4    0.07       0  4998.8    0.07       0  5008.5    0.07       0
  5122.7   0.035       0  5642.0    0.07       0
Bank Sta=4998.8,5008.5
Exp/Cntr=0.3,0.1

Type RM Length L Ch R = 1,29038,1020,1020,1020
BEGIN DESCRIPTION:
Mapping XS 8d7c28eb
END DESCRIPTION:
XS GIS Cut Line= 3
      1643492.74      7024961.31      1643707.56      7024483.93
      1644059.10      7023928.41
#Sta/Elev= 30
  4477.0 1566.12  4489.9 1565.93  4557.4 1565.40  4571.2 1564.83  4607.4 1564.24
  4617.1 1564.43  4634.2 1563.54  4663.4 1563.35  4700.0 1562.12  4789.1 1556.65
  4842.5 1552.95  4905.9 1550.27  4934.5 1549.72  4963.2 1549.85  4980.8 1548.59
  4996.1 1548.13  5026.2 1547.63  5026.7 1547.13  5035.7 1547.13  5036.2 1547.63
  5061.0 1548.78  5112.7 1549.53  5209.8 1552.41  5291.5 1554.91  5373.8 1556.77
  5418.4 1559.68  5467.8 1562.22  5534.5 1564.30  5650.5 1567.36  5657.9 1567.46
#Mann=12,-1,0
  4477.0   0.035       0  4489.9    0.07       0  4571.2   0.035       0
  4607.4    0.07       0  4789.1   0.035       0  4996.1    0.07       0
  5026.2    0.07       0  5036.2    0.07       0  5209.8   0.035       0
  5418.4    0.07       0  5534.5   0.035       0  5650.5    0.07       0
Bank Sta=5026.2,5036.2
Exp/Cntr=0.3,0.1

Type RM Length L Ch R = 1,28018,843,843,843
BEGIN DESCRIPTION:
Mapping XS d0ab347e
END DESCRIPTION:
XS GIS Cut Line= 3
      1643909.38      7025248.11      1644571.28      7024757.65
      1645113.80      7024477.71
#Sta/Elev= 30
  4173.3 1565.42  4293.9 1561.47  4449.3 1554.88  4641.2 1549.94  4664.2 1548.21
  4681.1 1548.04  4714.3 1547.62  4720.5 1546.80  4735.2 1548.23  4756.0 1547.52
  4806.1 1548.48  4906.3 1547.19  4935.5 1546.17  4956.3 1546.78  4985.6 1545.59
  4990.6 1544.18  4991.1 1543.68  5002.0 1544.18  5029.2 1547.18  5080.1 1550.07
  5140.0 1555.82  5162.2 1556.90  5186.7 1559.69  5223.0 1562.14  5273.0 1564.30
  5311.7 1567.35  5383.9 1569.78  5447.3 1570.88  5527.5 1570.89  5607.6 1571.11
#Mann=9,-1,0
  4173.3    0.07       0  4293.9   0.035       0  4681.1    0.16       0
  4956.3   0.035       0  4990.6   0.035       0  5002.0   0.035       0
  5186.7    0.07       0  5447.3   0.035       0  5527.5    0.07       0
Bank Sta=4990.6,5002
Exp/Cntr=0.3,0.1

Type RM Length L Ch R = 1,27175,728,728,728
BEGIN DESCRIPTION:
Mapping XS 2a74c616
END DESCRIPTION:
XS GIS Cut Line= 3
      1644491.41      7025913.26      1644853.40      7025475.75
      1645759.63      7025043.47
#Sta/Elev= 30
  4429.5 1570.99  4549.7 1571.06  4599.2 1570.08  4656.5 1567.41  4663.0 1566.01
  4720.4 1564.13  4726.9 1563.09  4776.5 1559.69  4805.0 1556.93  4851.7 1554.24
  4911.8 1550.23  4961.3 1543.67  4982.1 1542.07  4998.4 1541.75  4998.9 1541.25
  5010.1 1541.75  5049.6 1543.31  5163.1 1545.53  5185.7 1546.57  5198.6 1548.53
  5208.4 1547.57  5246.6 1549.15  5575.3 1560.51  5633.5 1563.66  5708.2 1569.61
  5763.6 1571.48  5792.4 1573.59  5839.1 1575.31  5928.5 1578.36  6001.4 1578.61
#Mann=7,-1,0
  4429.5   0.035       0  4776.5    0.07       0  4851.7   0.035       0
  4998.4   0.035       0  5010.1   0.035       0  5246.6    0.07       0
  5839.1   0.035       0
Bank Sta=4998.4,5010.1
Exp/Cntr=0.3,0.1

Type RM Length L Ch R = 1,26447,1003,1003,1003
BEGIN DESCRIPTION:
Mapping XS 89c25b37
END DESCRIPTION:
XS GIS Cut Line= 3
      1644862.57      7026440.68      1645303.12      7025982.77
      1645739.20      7025292.86
#Sta/Elev= 30
  4366.9 1575.09  4376.7 1575.42  4427.0 1572.12  4526.0 1563.55  4561.5 1561.83
  4589.8 1559.05  4596.8 1559.14  4695.8 1552.97  4806.9 1548.21  4950.5 1541.60
  5029.8 1539.88  5030.3 1539.38  5041.6 1539.88  5087.5 1540.23  5113.9 1543.37
  5185.4 1547.02  5216.9 1548.48  5312.2 1551.48  5333.3 1552.66  5354.5 1555.09
  5391.0 1556.45  5433.9 1559.57  5552.1 1563.69  5652.1 1568.95  5688.6 1571.49
  5709.8 1573.86  5740.3 1574.23  5788.8 1577.81  5811.3 1578.69  5818.5 1579.02
#Mann=9,-1,0
  4366.9   0.035       0  4376.7    0.07       0  4806.9   0.035       0
  5029.8   0.035       0  5041.6   0.035       0  5113.9    0.07       0
  5185.4   0.035       0  5216.9    0.07       0  5811.3   0.035       0
Bank Sta=5029.8,5041.6
Exp/Cntr=0.3,0.1

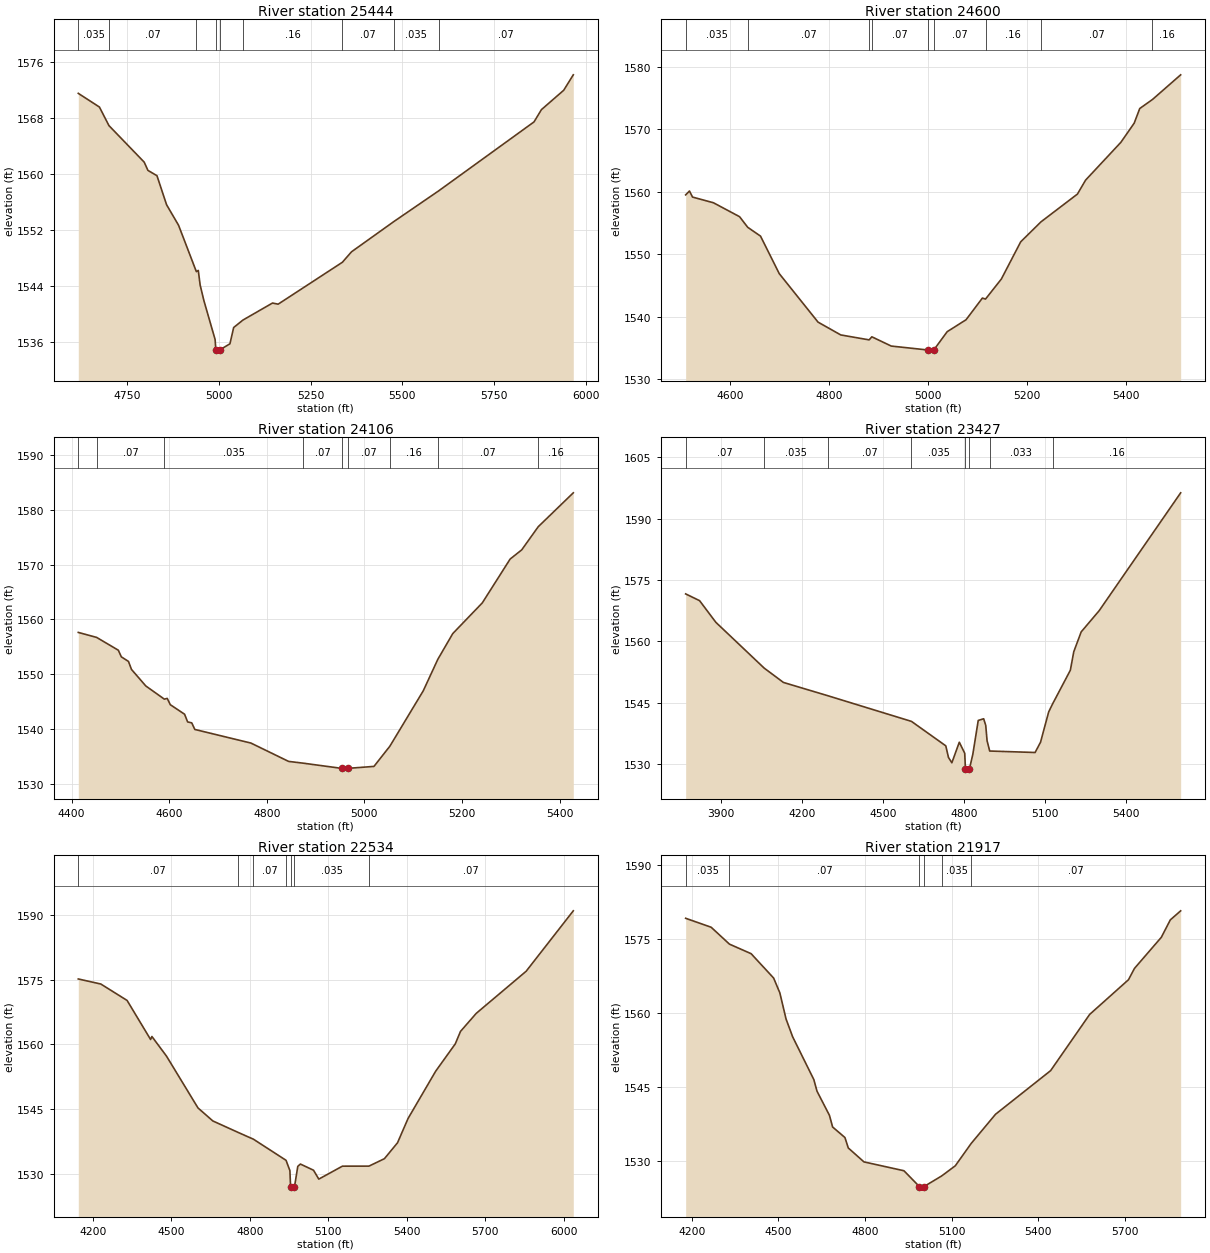
Type RM Length L Ch R = 1,25444,844,844,844
BEGIN DESCRIPTION:
Mapping XS 3fc1bc22
END DESCRIPTION:
XS GIS Cut Line= 3
      1645752.34      7026914.63      1645820.05      7026537.02
      1645952.75      7025582.13
#Sta/Elev= 30
  4617.5 1571.48  4675.0 1569.53  4701.0 1566.88  4797.0 1561.67  4807.1 1560.50
  4831.7 1559.74  4857.9 1555.60  4890.5 1552.68  4939.0 1546.06  4944.2 1546.24
  4949.3 1544.15  4959.5 1541.93  4990.0 1536.39  4992.0 1534.95  4992.5 1534.45
  5003.4 1534.45  5003.9 1534.95  5030.4 1535.78  5040.5 1538.10  5065.7 1539.16
  5146.3 1541.59  5161.7 1541.43  5336.5 1547.40  5361.3 1548.89  5477.1 1553.22
  5598.7 1557.58  5858.3 1567.41  5878.5 1569.16  5939.1 1571.92  5965.2 1574.12
#Mann=9,-1,0
  4617.5   0.035       0  4701.0    0.07       0  4939.0   0.035       0
  4992.0   0.035       0  5003.9   0.035       0  5065.7    0.16       0
  5336.5    0.07       0  5477.1   0.035       0  5598.7    0.07       0
Bank Sta=4992,5003.9
Exp/Cntr=0.3,0.1

Type RM Length L Ch R = 1,24600,494,494,494
BEGIN DESCRIPTION:
Mapping XS 2ce38e98
END DESCRIPTION:
XS GIS Cut Line= 3
      1646387.75      7026701.12      1646546.61      7026242.75
      1646695.05      7025747.96
#Sta/Elev= 30
  4509.8 1559.47  4517.5 1560.09  4523.7 1559.12  4566.0 1558.21  4618.9 1555.98
  4635.3 1554.29  4661.3 1552.87  4699.1 1546.88  4777.7 1539.11  4823.7 1537.06
  4881.1 1536.27  4886.6 1536.76  4925.9 1535.28  5000.0 1534.65  5000.5 1534.15
  5011.9 1534.65  5039.0 1537.58  5077.2 1539.49  5110.3 1542.96  5116.6 1542.80
  5148.6 1546.00  5187.8 1551.96  5228.9 1555.16  5302.6 1559.60  5319.1 1561.83
  5390.5 1567.88  5417.5 1570.95  5428.7 1573.29  5454.4 1574.73  5511.5 1578.68
#Mann=9,-1,0
  4509.8   0.035       0  4635.3    0.07       0  4881.1   0.035       0
  4886.6    0.07       0  5000.0    0.07       0  5011.9    0.07       0
  5116.6    0.16       0  5228.9    0.07       0  5454.4    0.16       0
Bank Sta=5000,5011.9
Exp/Cntr=0.3,0.1

Type RM Length L Ch R = 1,24106,679,679,679
BEGIN DESCRIPTION:
Chimney Creek 1174 47.0
END DESCRIPTION:
XS GIS Cut Line= 3
      1646537.48      7026634.08      1647010.18      7026287.57
      1647066.98      7025863.25
#Sta/Elev= 30
  4413.9 1557.64  4451.5 1556.73  4495.9 1554.40  4502.1 1553.19  4516.7 1552.36
  4522.9 1550.90  4552.2 1547.89  4590.2 1545.49  4596.2 1545.62  4602.4 1544.48
  4631.7 1542.74  4637.9 1541.34  4646.4 1541.17  4652.6 1539.97  4767.6 1537.49
  4844.8 1534.15  4874.6 1533.83  4953.8 1532.88  4954.3 1532.38  4965.8 1532.88
  5019.7 1533.24  5052.3 1536.92  5120.6 1546.99  5150.6 1552.75  5181.2 1557.43
  5241.7 1563.02  5298.7 1571.00  5322.4 1572.67  5356.3 1576.89  5428.1 1583.06
#Mann=9,-1,0
  4413.9   0.035       0  4451.5    0.07       0  4590.2   0.035       0
  4874.6    0.07       0  4953.8    0.07       0  4965.8    0.07       0
  5052.3    0.16       0  5150.6    0.07       0  5356.3    0.16       0
Bank Sta=4953.8,4965.8
Exp/Cntr=0.3,0.1

Type RM Length L Ch R = 1,23427,893,893,893
BEGIN DESCRIPTION:
Mapping XS 59f34453
END DESCRIPTION:
XS GIS Cut Line= 3
      1647444.72      7027899.46      1647538.47      7026677.21
      1647600.80      7026071.24
#Sta/Elev= 30
  3768.8 1571.59  3820.4 1569.94  3880.6 1564.66  4059.8 1553.47  4131.3 1549.96
  4294.8 1546.74  4605.9 1540.45  4733.1 1534.48  4743.1 1531.63  4755.6 1530.34
  4783.2 1535.36  4803.3 1532.67  4805.9 1528.80  4806.4 1528.30  4820.7 1528.80
  4833.4 1532.44  4853.4 1540.68  4873.5 1541.09  4881.2 1539.48  4886.2 1535.71
  4895.9 1533.21  5064.2 1532.85  5084.3 1535.36  5114.5 1542.76  5128.8 1544.69
  5194.9 1552.95  5207.5 1557.46  5235.1 1562.32  5301.6 1567.48  5603.8 1596.28
#Mann=8,-1,0
  3768.8    0.07       0  4059.8   0.035       0  4294.8    0.07       0
  4605.9   0.035       0  4805.9   0.033       0  4820.7   0.035       0
  4895.9   0.033       0  5128.8    0.16       0
Bank Sta=4805.9,4820.7
Exp/Cntr=0.3,0.1

Type RM Length L Ch R = 1,22534,617,617,617
BEGIN DESCRIPTION:
Mapping XS 99a46a14
END DESCRIPTION:
XS GIS Cut Line= 3
      1648173.89      7028093.85      1648100.97      7027239.71
      1648017.64      7026208.42
#Sta/Elev= 30
  4144.3 1575.15  4230.5 1573.98  4330.8 1570.18  4420.6 1561.13  4425.7 1561.82
  4481.4 1557.28  4601.8 1545.27  4658.7 1542.25  4754.5 1539.62  4813.6 1538.03
  4938.3 1533.14  4953.1 1530.74  4955.7 1526.96  4956.2 1526.46  4970.6 1526.96
  4983.2 1531.73  4993.2 1532.27  5043.4 1530.84  5063.5 1528.78  5153.8 1531.78
  5255.2 1531.79  5314.3 1533.51  5364.4 1537.20  5404.6 1542.82  5510.1 1553.77
  5585.2 1560.12  5605.2 1563.01  5665.4 1567.19  5856.0 1576.94  6036.2 1590.94
#Mann=7,-1,0
  4144.3    0.07       0  4754.5   0.035       0  4813.6    0.07       0
  4938.3   0.035       0  4955.7   0.035       0  4970.6   0.035       0
  5255.2    0.07       0
Bank Sta=4955.7,4970.6
Exp/Cntr=0.3,0.1

Type RM Length L Ch R = 1,21917,1047,1047,1047
BEGIN DESCRIPTION:
Mapping XS 483e1482
END DESCRIPTION:
XS GIS Cut Line= 3
      1648913.47      7027791.79      1648614.86      7027027.91
      1648385.70      7026163.34
#Sta/Elev= 30
  4179.1 1579.18  4267.4 1577.37  4330.8 1573.95  4405.8 1572.02  4483.8 1567.09
  4505.3 1564.10  4526.8 1558.81  4549.7 1555.20  4623.1 1546.54  4634.1 1544.19
  4677.1 1539.32  4688.1 1536.95  4730.8 1534.82  4742.4 1532.71  4796.7 1529.89
  4935.2 1528.10  4989.0 1524.88  4989.5 1524.38  5004.1 1524.88  5066.2 1527.06
  5113.0 1529.10  5168.2 1533.63  5252.5 1539.53  5443.2 1548.35  5578.5 1559.73
  5713.0 1566.75  5733.7 1569.04  5826.8 1575.34  5857.8 1578.85  5893.7 1580.69
#Mann=6,-1,0
  4179.1   0.035       0  4330.8    0.07       0  4989.0    0.07       0
  5004.1    0.07       0  5066.2   0.035       0  5168.2    0.07       0
Bank Sta=4989,5004.1
Exp/Cntr=0.3,0.1

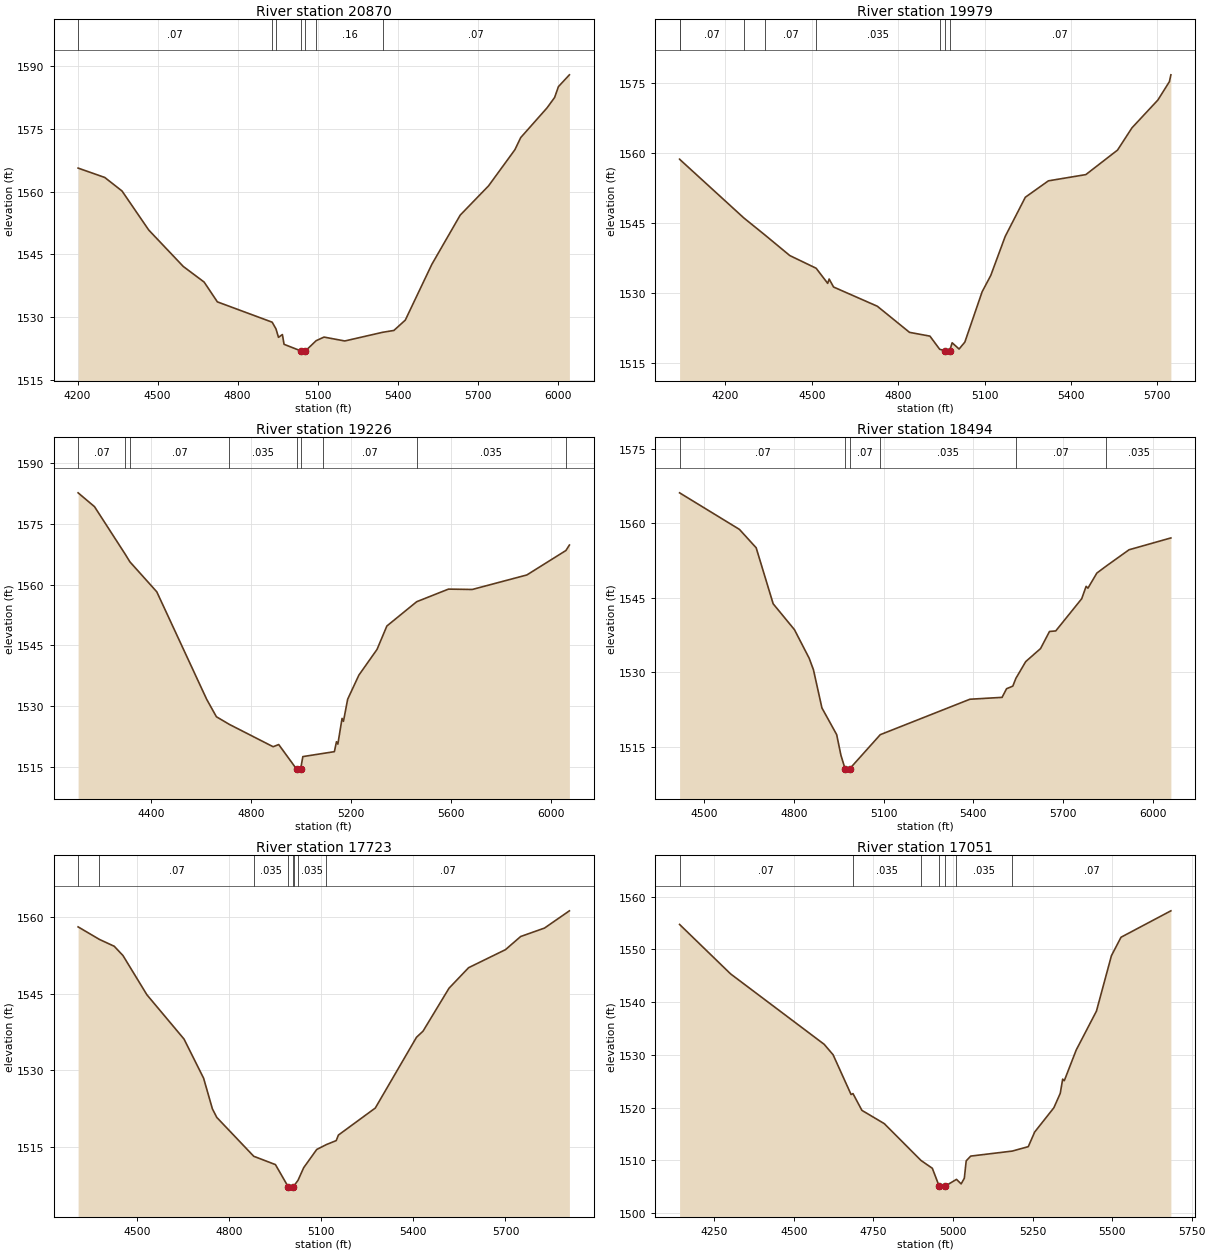
Type RM Length L Ch R = 1,20870,891,891,891
BEGIN DESCRIPTION:
Mapping XS a486111b
END DESCRIPTION:
XS GIS Cut Line= 3
      1649976.12      7027377.69      1649502.19      7026737.11
      1648813.11      7025951.82
#Sta/Elev= 30
  4201.9 1565.66  4301.8 1563.42  4366.5 1560.18  4466.7 1550.83  4596.1 1542.11
  4674.2 1538.38  4724.0 1533.63  4929.3 1528.77  4943.7 1527.16  4953.0 1525.14
  4967.7 1525.81  4973.9 1523.47  5038.1 1521.86  5038.6 1521.36  5053.5 1521.86
  5094.4 1524.35  5123.7 1525.20  5201.5 1524.27  5343.6 1526.35  5385.6 1526.79
  5428.3 1529.26  5527.9 1542.62  5634.2 1554.40  5740.5 1561.41  5839.2 1570.06
  5861.0 1572.96  5959.7 1580.08  5988.1 1582.57  6002.4 1585.17  6043.5 1587.99
#Mann=7,-1,0
  4201.9    0.07       0  4929.3   0.035       0  4943.7    0.07       0
  5038.1    0.07       0  5053.5    0.07       0  5094.4    0.16       0
  5343.6    0.07       0
Bank Sta=5038.1,5053.5
Exp/Cntr=0.3,0.1

Type RM Length L Ch R = 1,19979,753,753,753
BEGIN DESCRIPTION:
Mapping XS 0cc81658
END DESCRIPTION:
XS GIS Cut Line= 3
      1650204.88      7027325.41      1650048.63      7026382.72
      1650033.01      7025632.83
#Sta/Elev= 30
  4041.3 1558.64  4041.6 1558.61  4264.3 1546.06  4338.9 1542.34  4423.9 1538.00
  4515.4 1535.28  4555.5 1532.04  4560.5 1532.97  4575.9 1531.26  4727.9 1527.14
  4839.5 1521.55  4910.4 1520.74  4944.3 1517.92  4963.3 1517.60  4963.8 1517.10
  4979.1 1517.60  4987.5 1519.32  5011.6 1517.98  5031.6 1519.46  5091.6 1530.24
  5121.6 1533.74  5171.6 1542.08  5241.6 1550.49  5321.6 1554.00  5451.7 1555.34
  5561.7 1560.59  5611.7 1565.35  5701.7 1571.31  5741.7 1575.24  5746.9 1576.71
#Mann=8,-1,0
  4041.3   0.035       0  4041.6    0.07       0  4264.3   0.035       0
  4338.9    0.07       0  4515.4   0.035       0  4944.3    0.07       0
  4963.3    0.07       0  4979.1    0.07       0
Bank Sta=4963.3,4979.1
Exp/Cntr=0.3,0.1

Type RM Length L Ch R = 1,19226,732,732,732
BEGIN DESCRIPTION:
Mapping XS 66640d96
END DESCRIPTION:
XS GIS Cut Line= 3
      1651098.31      7027392.02      1650715.51      7026589.97
      1650236.36      7025626.45
#Sta/Elev= 30
  4109.1 1582.68  4174.7 1579.26  4295.3 1567.72  4316.3 1565.62  4423.8 1558.21
  4623.3 1531.64  4662.2 1527.33  4714.1 1525.44  4889.1 1519.92  4911.4 1520.46
  4982.9 1514.39  4983.4 1513.89  4998.9 1514.39  5007.9 1517.48  5089.3 1518.27
  5134.0 1518.70  5142.3 1521.15  5147.9 1520.57  5164.7 1526.92  5170.3 1526.20
  5187.1 1531.66  5231.9 1537.61  5304.6 1543.98  5343.9 1549.76  5463.3 1555.77
  5590.2 1558.88  5685.4 1558.79  5903.8 1562.38  6059.9 1568.42  6073.9 1569.77
#Mann=9,-1,0
  4109.1    0.07       0  4295.3   0.035       0  4316.3    0.07       0
  4714.1   0.035       0  4982.9   0.035       0  4998.9   0.035       0
  5089.3    0.07       0  5463.3   0.035       0  6059.9    0.07       0
Bank Sta=4982.9,4998.9
Exp/Cntr=0.3,0.1

Type RM Length L Ch R = 1,18494,771,771,771
BEGIN DESCRIPTION:
Mapping XS 47ccd4e9
END DESCRIPTION:
XS GIS Cut Line= 3
      1651816.35      7026798.88      1651381.44      7026413.45
      1650503.87      7025814.52
#Sta/Elev= 30
  4417.6 1566.12  4617.8 1558.76  4673.8 1555.06  4730.7 1543.78  4801.8 1538.58
  4851.1 1532.83  4865.4 1530.51  4893.8 1522.82  4943.1 1517.45  4957.4 1513.29
  4971.1 1510.60  4971.6 1510.10  4987.1 1510.60  5089.0 1517.44  5388.8 1524.57
  5496.5 1524.95  5511.5 1526.69  5532.4 1527.21  5542.6 1528.77  5575.6 1532.15
  5625.2 1534.77  5655.1 1538.21  5676.0 1538.32  5762.8 1544.80  5777.7 1547.30
  5783.7 1546.93  5813.6 1549.97  5845.7 1551.41  5921.3 1554.66  6061.2 1557.04
#Mann=6,-1,0
  4417.6    0.07       0  4971.1    0.07       0  4987.1    0.07       0
  5089.0   0.035       0  5542.6    0.07       0  5845.7   0.035       0
Bank Sta=4971.1,4987.1
Exp/Cntr=0.3,0.1

Type RM Length L Ch R = 1,17723,672,672,672
BEGIN DESCRIPTION:
Mapping XS f70867b8
END DESCRIPTION:
XS GIS Cut Line= 3
      1652204.38      7026314.52      1651753.84      7025778.04
      1651110.60      7025147.81
#Sta/Elev= 30
  4307.3 1558.10  4376.6 1555.65  4424.9 1554.31  4453.5 1552.49  4531.5 1544.81
  4652.5 1536.14  4716.3 1528.48  4744.9 1522.49  4759.2 1520.81  4879.7 1513.20
  4950.4 1511.57  4991.6 1507.27  4992.1 1506.77  5008.1 1507.27  5010.7 1507.42
  5023.8 1508.47  5042.5 1510.97  5084.9 1514.53  5116.1 1515.48  5148.5 1516.27
  5155.6 1517.35  5275.8 1522.64  5410.2 1536.50  5431.3 1537.68  5516.2 1546.10
  5579.9 1550.11  5700.1 1553.64  5749.5 1556.21  5827.4 1557.87  5908.4 1561.24
#Mann=8,-1,0
  4307.3   0.035       0  4376.6    0.07       0  4879.7   0.035       0
  4991.6   0.035       0  5008.1   0.035       0  5010.7    0.07       0
  5023.8   0.035       0  5116.1    0.07       0
Bank Sta=4991.6,5008.1
Exp/Cntr=0.3,0.1

Type RM Length L Ch R = 1,17051,926,926,926
BEGIN DESCRIPTION:
Mapping XS 3faacdd3
END DESCRIPTION:
XS GIS Cut Line= 3
      1652400.75      7026287.32      1652304.40      7025435.81
      1652236.80      7024751.99
#Sta/Elev= 30
  4140.6 1554.72  4300.9 1545.35  4594.9 1532.01  4623.0 1530.03  4679.6 1522.49
  4685.6 1522.66  4713.6 1519.49  4784.0 1516.97  4899.4 1509.99  4935.0 1508.51
  4956.8 1505.06  4957.3 1504.56  4973.5 1505.06  5010.9 1506.41  5025.5 1505.55
  5035.5 1506.62  5041.4 1509.92  5055.6 1510.82  5186.1 1511.77  5236.5 1512.61
  5256.6 1515.38  5316.9 1519.98  5337.0 1522.71  5344.6 1525.40  5349.7 1525.11
  5387.2 1530.93  5450.7 1538.29  5497.8 1548.79  5527.9 1552.29  5684.7 1557.30
#Mann=7,-1,0
  4140.6    0.07       0  4685.6   0.035       0  4899.4    0.07       0
  4956.8    0.07       0  4973.5    0.07       0  5010.9   0.035       0
  5186.1    0.07       0
Bank Sta=4956.8,4973.5
Exp/Cntr=0.3,0.1