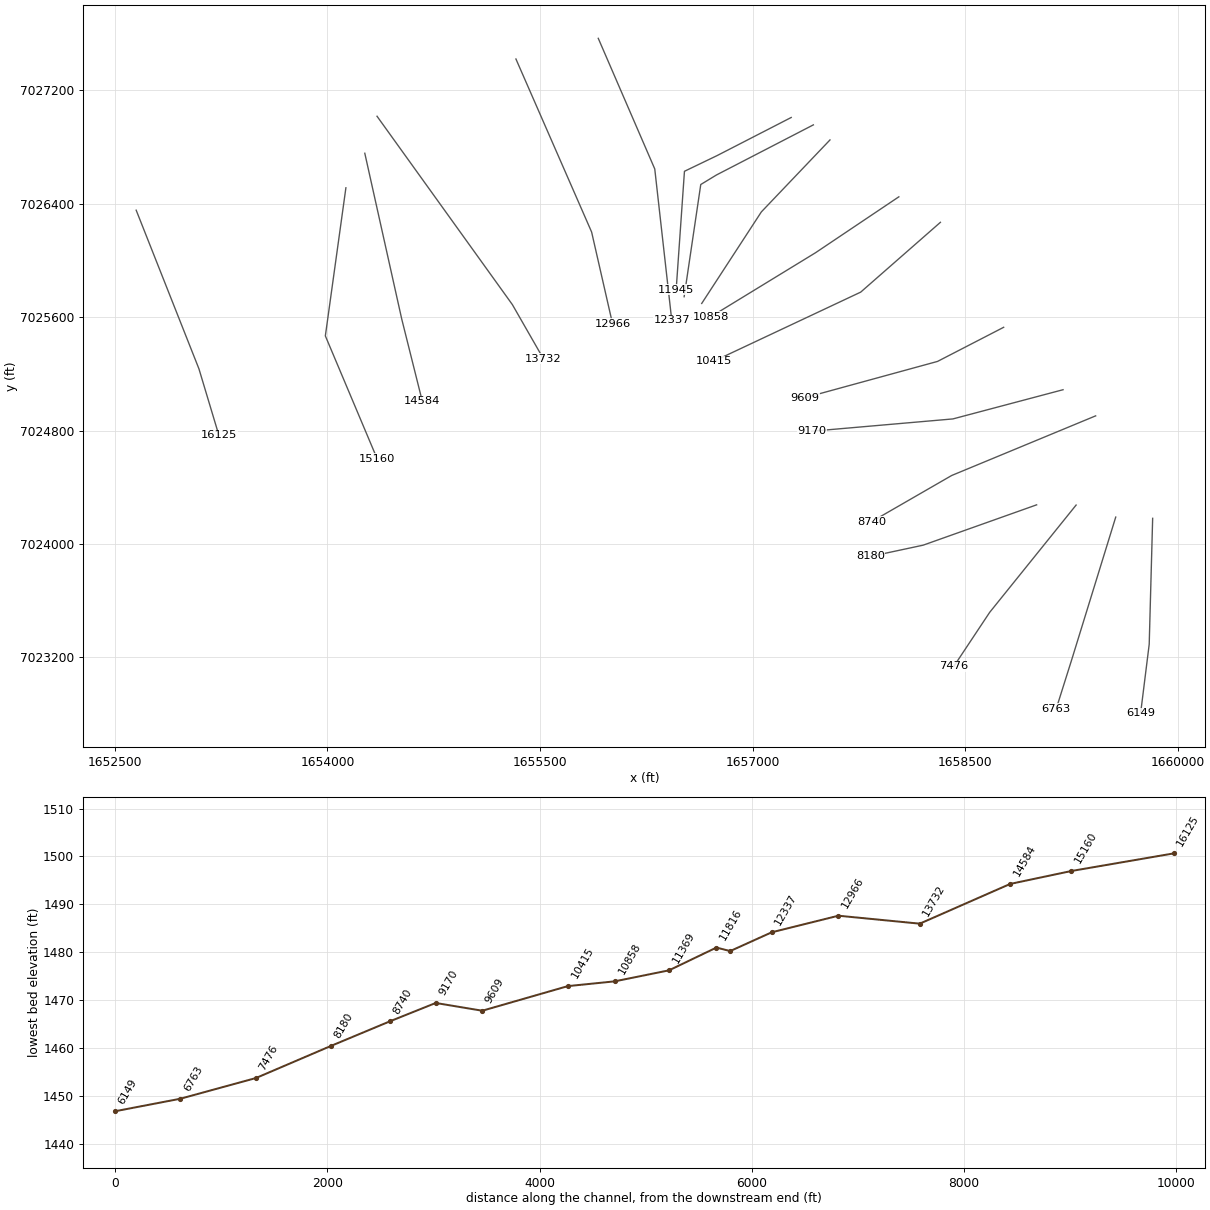
HEC-RAS study Chimney Creek 1174.prj: Chimney Creek 1174 Base Level Engineering

--- Chimney Creek 1174.g01 (geometry) --- (continued)

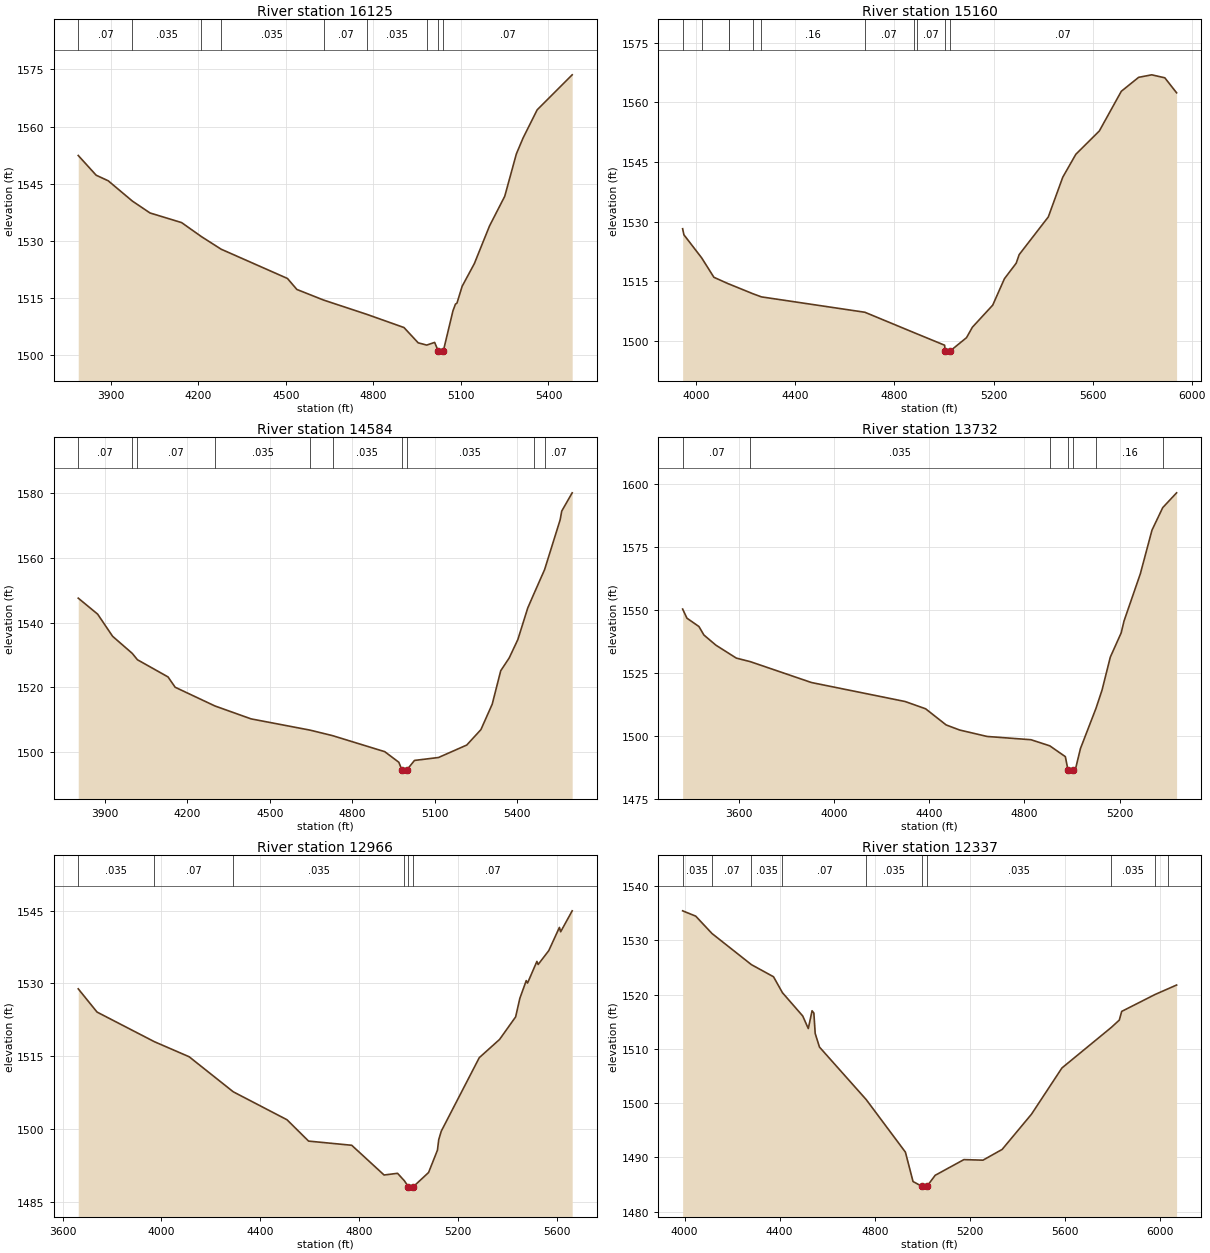
Type RM Length L Ch R = 1,16125,965,965,965
BEGIN DESCRIPTION:
Mapping XS c97f2908
END DESCRIPTION:
XS GIS Cut Line= 3
      1652650.76      7026355.07      1653093.47      7025235.29
      1653234.09      7024766.55
#Sta/Elev= 30
  3787.8 1552.43  3849.2 1547.26  3890.7 1545.79  3973.5 1540.47  4033.9 1537.36
  4142.1 1534.84  4210.0 1531.17  4277.8 1527.86  4505.1 1520.19  4537.4 1517.31
  4629.0 1514.53  4778.2 1510.76  4904.6 1507.33  4953.3 1503.32  4982.5 1502.73
  5009.7 1503.43  5022.4 1501.12  5022.9 1500.62  5039.3 1501.12  5072.6 1511.73
  5081.0 1513.45  5086.3 1513.73  5103.9 1518.12  5145.7 1524.06  5197.9 1533.96
  5250.1 1541.74  5289.9 1552.84  5312.7 1556.98  5361.2 1564.39  5481.3 1573.57
#Mann=9,-1,0
  3787.8    0.07       0  3973.5   0.035       0  4210.0    0.07       0
  4277.8   0.035       0  4629.0    0.07       0  4778.2   0.035       0
  4982.5    0.07       0  5022.4    0.07       0  5039.3    0.07       0
Bank Sta=5022.4,5039.3
Exp/Cntr=0.3,0.1

Type RM Length L Ch R = 1,15160,576,576,576
BEGIN DESCRIPTION:
Chimney Creek 1174 28.0
END DESCRIPTION:
XS GIS Cut Line= 3
      1654130.00      7026513.03      1653985.07      7025467.83
      1654349.70      7024602.30
#Sta/Elev= 30
  3944.8 1528.23  3949.9 1526.71  4021.9 1520.88  4071.0 1516.02  4131.0 1514.34
  4131.9 1514.33  4230.2 1511.84  4262.9 1511.09  4680.7 1507.22  4877.3 1502.14
  4889.4 1501.83  5002.6 1498.93  5004.5 1497.44  5005.0 1496.94  5024.2 1497.44
  5091.0 1500.83  5114.7 1503.46  5196.8 1509.01  5244.2 1515.67  5291.7 1519.57
  5303.6 1521.72  5421.2 1531.20  5479.5 1541.18  5532.4 1546.96  5627.3 1552.83
  5716.0 1562.81  5786.0 1566.32  5838.9 1566.95  5891.7 1566.20  5939.2 1562.43
#Mann=11,-1,0
  3944.8   0.035       0  4021.9    0.07       0  4131.0   0.035       0
  4131.9    0.07       0  4230.2   0.035       0  4262.9    0.16       0
  4680.7    0.07       0  4877.3    0.16       0  4889.4    0.07       0
  5004.5    0.07       0  5024.2    0.07       0
Bank Sta=5004.5,5024.2
Exp/Cntr=0.3,0.1

Type RM Length L Ch R = 1,14584,852,852,852
BEGIN DESCRIPTION:
Mapping XS 14094990
END DESCRIPTION:
XS GIS Cut Line= 3
      1654263.25      7026757.00      1654523.67      7025587.27
      1654669.08      7025005.63
#Sta/Elev= 30
  3802.4 1547.51  3873.1 1542.58  3927.5 1535.76  3999.0 1530.50  4017.9 1528.54
  4129.2 1523.25  4155.2 1520.07  4300.1 1514.30  4431.5 1510.33  4646.4 1506.86
  4728.0 1505.17  4918.1 1500.23  4969.3 1496.97  4979.9 1494.74  4980.4 1494.24
  4999.7 1494.74  5026.3 1497.53  5113.9 1498.44  5216.5 1502.27  5268.0 1507.01
  5309.2 1514.85  5340.2 1525.15  5371.1 1529.10  5402.5 1534.76  5438.6 1544.49
  5459.8 1548.61  5499.8 1556.28  5556.6 1571.66  5562.3 1574.33  5600.3 1579.94
#Mann=10,-1,0
  3802.4    0.07       0  3999.0   0.035       0  4017.9    0.07       0
  4300.1   0.035       0  4646.4    0.07       0  4728.0   0.035       0
  4979.9    0.07       0  4999.7   0.035       0  5459.8    0.16       0
  5499.8    0.07       0
Bank Sta=4979.9,4999.7
Exp/Cntr=0.3,0.1

Type RM Length L Ch R = 1,13732,766,766,766
BEGIN DESCRIPTION:
Mapping XS 0dfac69e
END DESCRIPTION:
XS GIS Cut Line= 3
      1654349.57      7027018.06      1655304.42      7025688.21
      1655523.17      7025306.26
#Sta/Elev= 30
  3362.5 1550.22  3380.7 1546.59  3431.1 1543.29  3451.9 1539.93  3502.3 1535.90
  3588.2 1530.77  3647.1 1529.36  3904.2 1521.08  4298.2 1513.55  4384.4 1510.66
  4470.5 1504.27  4527.5 1502.24  4642.9 1499.69  4827.6 1498.39  4906.4 1495.98
  4972.0 1491.68  4983.0 1486.44  4983.5 1485.94  5002.8 1486.44  5014.0 1486.54
  5035.6 1494.92  5101.1 1510.91  5126.2 1518.06  5161.2 1531.19  5206.8 1540.78
  5218.8 1545.50  5287.4 1564.23  5336.3 1581.51  5381.5 1590.45  5439.8 1596.32
#Mann=7,-1,0
  3362.5    0.07       0  3647.1   0.035       0  4906.4    0.07       0
  4983.0    0.07       0  5002.8    0.07       0  5101.1    0.16       0
  5381.5    0.07       0
Bank Sta=4983,5002.8
Exp/Cntr=0.3,0.1

Type RM Length L Ch R = 1,12966,629,629,629
BEGIN DESCRIPTION:
Mapping XS 88c86442
END DESCRIPTION:
XS GIS Cut Line= 3
      1655329.31      7027422.15      1655863.16      7026200.80
      1656011.22      7025551.39
#Sta/Elev= 30
  3663.2 1528.89  3739.3 1524.10  3971.4 1517.99  4112.0 1514.89  4290.7 1507.66
  4508.1 1501.90  4595.4 1497.50  4770.0 1496.64  4901.0 1490.51  4955.5 1490.86
  4983.1 1489.32  4999.4 1488.10  4999.9 1487.60  5019.2 1488.10  5081.1 1491.03
  5116.9 1495.63  5122.1 1497.79  5132.3 1499.54  5286.2 1514.70  5368.2 1518.45
  5433.3 1523.10  5450.3 1526.91  5476.3 1530.59  5481.5 1530.07  5519.4 1534.54
  5524.5 1533.91  5567.5 1536.77  5610.5 1541.55  5615.6 1540.65  5662.2 1544.97
#Mann=6,-1,0
  3663.2   0.035       0  3971.4    0.07       0  4290.7   0.035       0
  4983.1    0.07       0  4999.4    0.07       0  5019.2    0.07       0
Bank Sta=4999.4,5019.2
Exp/Cntr=0.3,0.1

Type RM Length L Ch R = 1,12337,392,392,392
BEGIN DESCRIPTION:
Mapping XS b67dfb85
END DESCRIPTION:
XS GIS Cut Line= 3
      1655910.02      7027568.02      1656308.47      7026646.11
      1656428.26      7025578.44
#Sta/Elev= 30
  3991.8 1535.44  4046.9 1534.46  4115.3 1531.26  4281.2 1525.52  4374.2 1523.29
  4411.8 1520.35  4497.1 1516.06  4520.6 1513.74  4536.5 1517.02  4544.1 1516.59
  4549.6 1512.84  4567.6 1510.33  4764.6 1500.63  4929.3 1490.96  4961.4 1485.54
  4999.5 1484.64  5000.0 1484.14  5019.7 1484.64  5054.6 1486.69  5175.4 1489.58
  5255.9 1489.48  5336.4 1491.46  5460.2 1497.97  5587.9 1506.47  5796.1 1513.96
  5829.4 1515.30  5839.5 1516.90  5980.0 1520.02  6034.5 1521.07  6070.5 1521.76
#Mann=10,-1,0
  3991.8   0.035       0  4115.3    0.07       0  4281.2   0.035       0
  4411.8    0.07       0  4764.6   0.035       0  4999.5   0.035       0
  5019.7   0.035       0  5796.1   0.035       0  5980.0    0.07       0
  6034.5   0.035       0
Bank Sta=4999.5,5019.7
Exp/Cntr=0.3,0.1

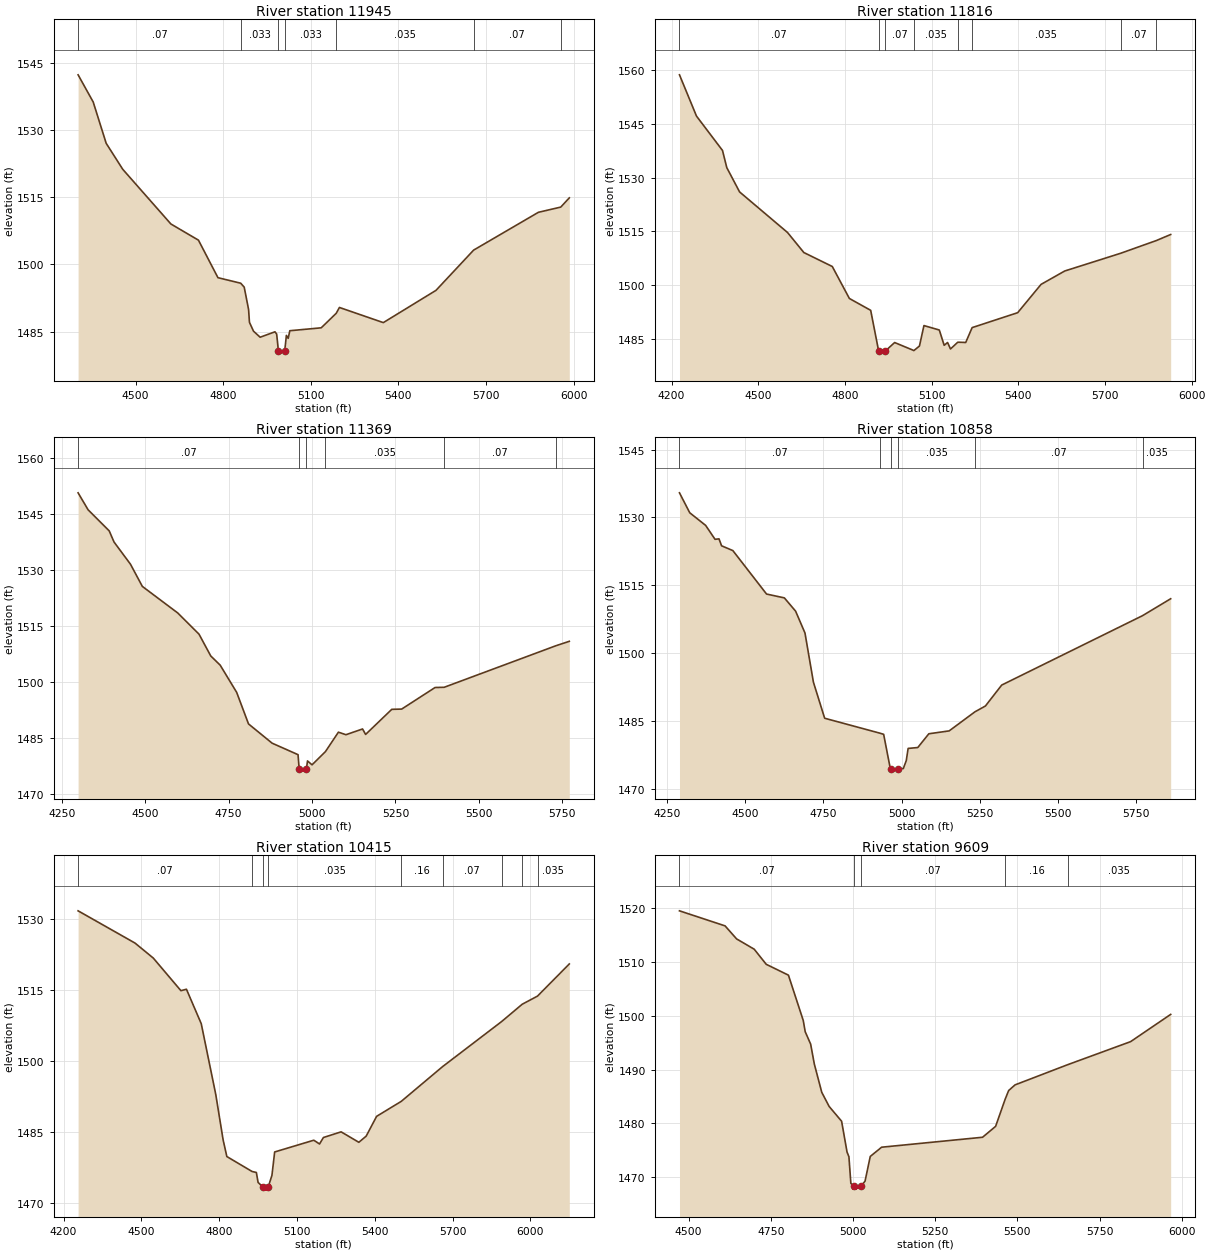
Type RM Length L Ch R = 1,11945,129,129,129
BEGIN DESCRIPTION:
Mapping XS dfeb1d2a
END DESCRIPTION:
XS GIS Cut Line= 4
      1657270.93      7027009.37      1656747.95      7026740.29
      1656517.92      7026629.61      1656459.36      7025792.48
#Sta/Elev= 30
  4303.0 1542.32  4354.7 1536.26  4399.2 1527.04  4455.9 1521.24  4620.9 1509.03
  4715.3 1505.42  4782.0 1497.05  4860.1 1495.81  4872.0 1494.94  4887.0 1489.94
  4890.0 1487.07  4904.0 1485.10  4926.6 1483.76  4977.4 1484.97  4983.2 1484.46
  4989.2 1480.71  4989.7 1480.21  5010.8 1480.71  5016.5 1484.17  5022.7 1483.51
  5028.2 1485.21  5135.8 1485.86  5187.1 1489.09  5198.2 1490.40  5348.5 1487.02
  5529.0 1494.22  5657.9 1503.20  5879.8 1511.64  5956.3 1512.80  5985.6 1514.86
#Mann=7,-1,0
  4303.0    0.07       0  4860.1   0.033       0  4989.2   0.033       0
  5010.8   0.033       0  5187.1   0.035       0  5657.9    0.07       0
  5956.3   0.035       0
Bank Sta=4989.2,5010.8
Exp/Cntr=0.3,0.1

Type RM Length L Ch R = 1,11816,447,447,447
BEGIN DESCRIPTION:
Mapping XS 38983a23
END DESCRIPTION:
XS GIS Cut Line= 4
      1657427.22      7026957.31      1656743.61      7026603.57
      1656632.93      7026536.29      1656515.75      7025744.24
#Sta/Elev= 30
  4227.5 1558.72  4286.3 1547.20  4376.4 1537.58  4391.2 1532.79  4435.5 1526.00
  4601.4 1514.66  4657.9 1509.06  4756.3 1505.16  4815.5 1496.22  4889.2 1492.91
  4917.0 1481.45  4917.5 1480.95  4938.6 1481.45  4972.1 1483.91  5038.8 1481.67
  5058.0 1482.94  5073.5 1488.65  5126.7 1487.41  5143.5 1483.14  5155.3 1483.92
  5165.4 1482.11  5190.6 1484.00  5218.1 1483.93  5240.3 1488.08  5397.9 1492.25
  5478.8 1500.16  5560.7 1503.90  5753.8 1508.84  5877.8 1512.41  5927.4 1514.10
#Mann=8,-1,0
  4227.5    0.07       0  4917.0    0.07       0  4938.6    0.07       0
  5038.8   0.035       0  5190.6    0.07       0  5240.3   0.035       0
  5753.8    0.07       0  5877.8   0.035       0
Bank Sta=4917,4938.6
Exp/Cntr=0.3,0.1

Type RM Length L Ch R = 1,11369,511,511,511
BEGIN DESCRIPTION:
Mapping XS 3b7ab0c7
END DESCRIPTION:
XS GIS Cut Line= 3
      1657544.36      7026850.93      1657060.45      7026343.15
      1656639.71      7025696.87
#Sta/Elev= 30
  4298.7 1550.78  4328.7 1546.23  4392.0 1540.58  4406.4 1537.60  4455.8 1531.64
  4491.3 1525.70  4597.3 1518.59  4661.2 1512.90  4696.4 1507.06  4724.7 1504.59
  4774.1 1497.30  4809.6 1488.84  4880.4 1483.68  4958.1 1480.60  4961.5 1476.69
  4962.0 1476.19  4983.1 1476.69  4986.4 1478.92  5000.1 1477.88  5040.2 1481.42
  5079.1 1486.63  5101.7 1485.95  5151.5 1487.49  5160.7 1486.03  5239.1 1492.75
  5268.8 1492.82  5368.9 1498.60  5396.2 1498.66  5732.2 1509.83  5771.3 1510.98
#Mann=6,-1,0
  4298.7    0.07       0  4961.5    0.07       0  4983.1    0.07       0
  5040.2   0.035       0  5396.2    0.07       0  5732.2   0.035       0
Bank Sta=4961.5,4983.1
Exp/Cntr=0.3,0.1

Type RM Length L Ch R = 1,10858,443,443,443
BEGIN DESCRIPTION:
Mapping XS f0b260b9
END DESCRIPTION:
XS GIS Cut Line= 3
      1658030.14      7026449.48      1657442.03      7026054.52
      1656704.18      7025603.13
#Sta/Elev= 30
  4288.7 1535.45  4321.6 1531.04  4372.6 1528.24  4402.6 1525.17  4415.3 1525.27
  4423.6 1523.73  4459.6 1522.68  4567.6 1513.06  4624.7 1512.21  4660.7 1509.27
  4690.7 1504.44  4717.7 1493.58  4753.7 1485.59  4931.0 1482.28  4942.7 1482.03
  4963.7 1474.56  4967.8 1474.39  4968.3 1473.89  4989.5 1474.39  5005.6 1474.45
  5015.2 1476.23  5021.1 1478.91  5052.0 1479.11  5087.4 1482.15  5152.6 1482.79
  5234.9 1487.00  5268.7 1488.30  5320.9 1492.93  5772.0 1508.28  5862.1 1512.02
#Mann=6,-1,0
  4288.7    0.07       0  4931.0   0.035       0  4967.8   0.035       0
  4989.5   0.035       0  5234.9    0.07       0  5772.0   0.035       0
Bank Sta=4967.8,4989.5
Exp/Cntr=0.3,0.1

Type RM Length L Ch R = 1,10415,806,806,806
BEGIN DESCRIPTION:
Mapping XS 617ad29f
END DESCRIPTION:
XS GIS Cut Line= 3
      1658323.11      7026269.37      1657761.04      7025776.75
      1656723.71      7025288.46
#Sta/Elev= 30
  4256.1 1531.83  4475.6 1525.00  4546.1 1521.82  4652.5 1514.92  4673.9 1515.22
  4730.9 1507.93  4786.9 1492.94  4815.3 1483.31  4829.6 1479.79  4927.1 1476.62
  4943.4 1476.42  4950.1 1474.31  4967.7 1473.39  4968.2 1472.89  4989.4 1473.39
  5003.5 1475.81  5014.0 1480.76  5164.9 1483.25  5187.0 1482.45  5201.9 1483.82
  5270.2 1485.02  5338.6 1482.81  5366.9 1484.12  5407.0 1488.30  5502.4 1491.49
  5661.3 1498.83  5889.3 1508.39  5968.5 1512.05  6027.4 1513.77  6150.0 1520.58
#Mann=9,-1,0
  4256.1    0.07       0  4927.1   0.035       0  4967.7   0.035       0
  4989.4   0.035       0  5502.4    0.16       0  5661.3    0.07       0
  5889.3   0.035       0  5968.5    0.07       0  6027.4   0.035       0
Bank Sta=4967.7,4989.4
Exp/Cntr=0.3,0.1

Type RM Length L Ch R = 1,9609,439,439,439
BEGIN DESCRIPTION:
Mapping XS 90b4f87a
END DESCRIPTION:
XS GIS Cut Line= 3
      1658769.41      7025528.49      1658302.82      7025287.60
      1657368.70      7025031.85
#Sta/Elev= 30
  4472.5 1519.53  4611.1 1516.73  4646.3 1514.30  4699.7 1512.39  4736.3 1509.58
  4803.8 1507.56  4848.8 1499.14  4854.8 1497.04  4871.3 1494.74  4882.6 1491.01
  4905.1 1485.77  4927.6 1483.13  4965.5 1480.38  4982.0 1474.65  4987.7 1473.79
  4993.6 1468.84  5002.0 1468.25  5002.5 1467.75  5023.9 1468.25  5036.8 1469.24
  5052.6 1473.83  5087.1 1475.55  5394.1 1477.40  5433.8 1479.43  5462.4 1484.41
  5473.4 1486.09  5493.0 1487.15  5653.2 1490.91  5844.2 1495.19  5966.1 1500.26
#Mann=5,-1,0
  4472.5    0.07       0  5002.0    0.07       0  5023.9    0.07       0
  5462.4    0.16       0  5653.2   0.035       0
Bank Sta=5002,5023.9
Exp/Cntr=0.3,0.1

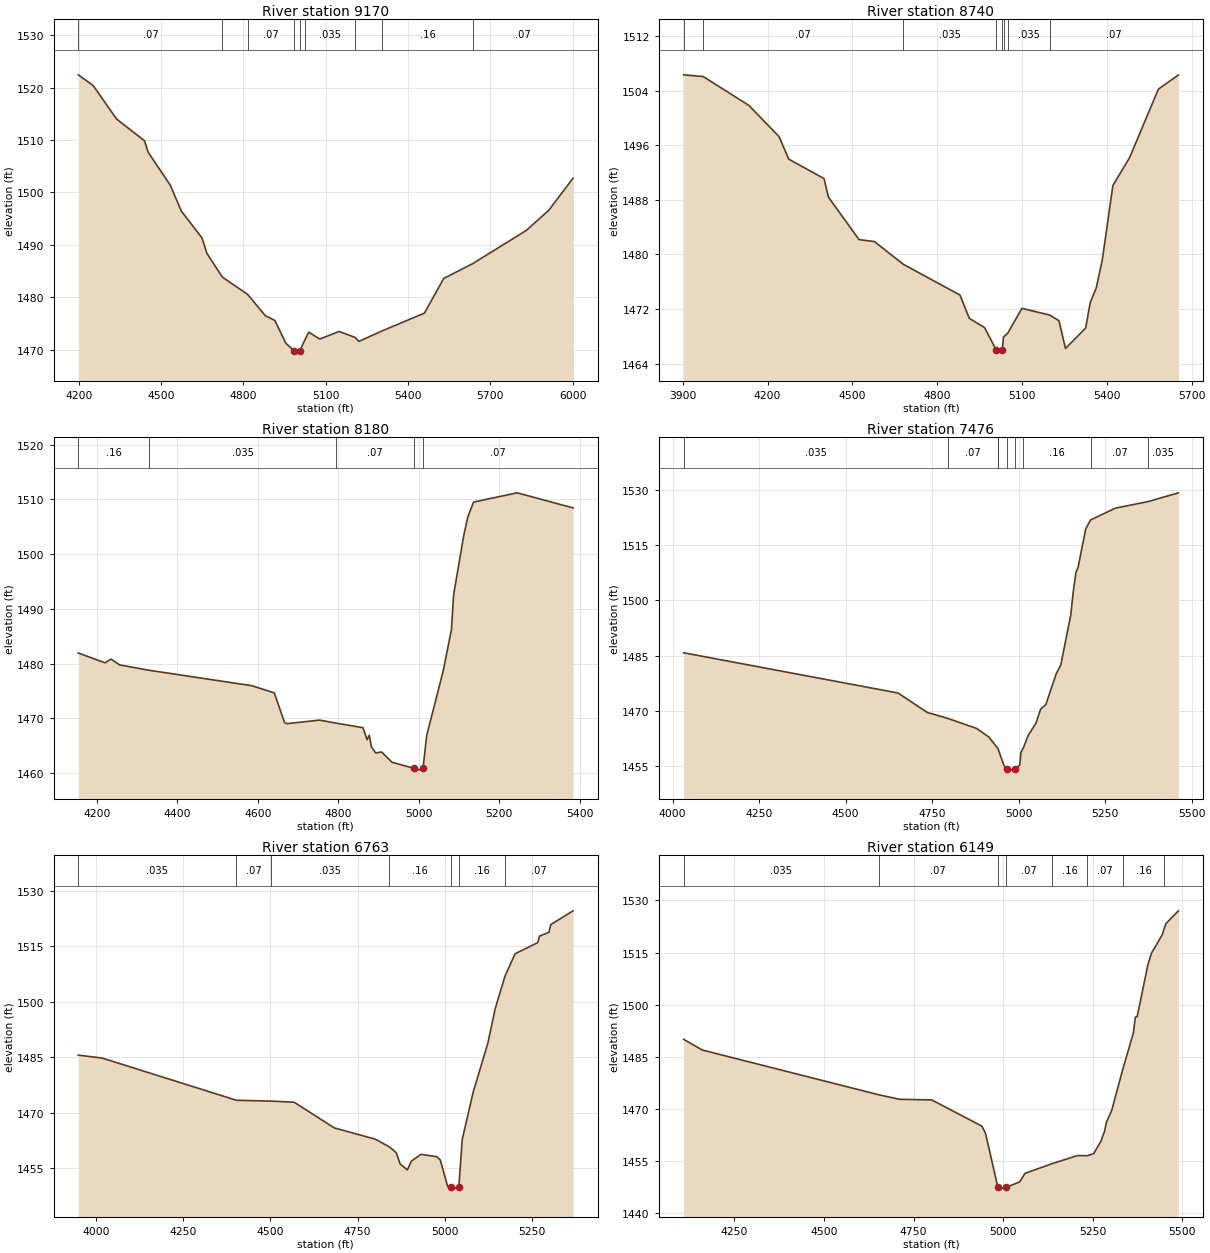
Type RM Length L Ch R = 1,9170,430,430,430
BEGIN DESCRIPTION:
Mapping XS 99c043c4
END DESCRIPTION:
XS GIS Cut Line= 3
      1659188.24      7025087.94      1658411.33      7024881.78
      1657415.20      7024794.97
#Sta/Elev= 30
  4197.9 1522.43  4252.0 1520.40  4337.5 1514.00  4439.2 1509.87  4452.9 1507.65
  4533.3 1501.39  4573.7 1496.45  4648.7 1491.35  4666.8 1488.40  4723.5 1483.85
  4815.0 1480.58  4879.5 1476.52  4914.5 1475.60  4954.7 1471.25  4983.9 1469.87
  4984.4 1469.37  5005.8 1469.87  5026.1 1472.12  5038.2 1473.37  5078.3 1472.05
  5148.6 1473.51  5207.4 1472.35  5220.9 1471.61  5306.6 1473.63  5459.8 1477.00
  5530.0 1483.60  5636.3 1486.45  5831.2 1492.77  5912.8 1496.59  6001.6 1502.73
#Mann=9,-1,0
  4197.9    0.07       0  4723.5   0.035       0  4815.0    0.07       0
  4983.9    0.07       0  5005.8    0.07       0  5026.1   0.035       0
  5207.4    0.07       0  5306.6    0.16       0  5636.3    0.07       0
Bank Sta=4983.9,5005.8
Exp/Cntr=0.3,0.1

Type RM Length L Ch R = 1,8740,560,560,560
BEGIN DESCRIPTION:
Mapping XS be9235d6
END DESCRIPTION:
XS GIS Cut Line= 3
      1659418.25      7024903.47      1658402.65      7024482.47
      1657839.19      7024157.41
#Sta/Elev= 30
  3903.2 1506.32  3972.6 1506.07  4134.0 1501.84  4240.4 1497.29  4275.1 1493.97
  4399.9 1491.12  4415.5 1488.40  4523.7 1482.18  4577.9 1481.90  4680.1 1478.57
  4881.0 1474.05  4913.5 1470.65  4967.6 1469.29  5008.4 1466.05  5008.9 1465.55
  5030.4 1466.05  5034.7 1467.92  5049.4 1468.45  5099.8 1472.11  5198.0 1471.13
  5230.8 1470.30  5253.9 1466.23  5325.3 1469.23  5341.1 1472.91  5362.6 1475.10
  5384.2 1479.25  5421.5 1490.11  5480.4 1494.17  5582.4 1504.22  5653.1 1506.30
#Mann=8,-1,0
  3903.2   0.035       0  3972.6    0.07       0  4680.1   0.035       0
  5008.4   0.035       0  5030.4   0.035       0  5034.7    0.07       0
  5049.4   0.035       0  5198.0    0.07       0
Bank Sta=5008.4,5030.4
Exp/Cntr=0.3,0.1

Type RM Length L Ch R = 1,8180,704,704,704
BEGIN DESCRIPTION:
Mapping XS e846a9b9
END DESCRIPTION:
XS GIS Cut Line= 3
      1659001.86      7024275.41      1658201.52      7023990.69
      1657829.12      7023911.02
#Sta/Elev= 30
  4153.3 1481.95  4219.6 1480.16  4234.9 1480.83  4256.1 1479.77  4329.5 1478.79
  4585.1 1475.97  4640.7 1474.66  4666.2 1469.25  4671.5 1469.03  4753.4 1469.69
  4795.2 1469.12  4861.1 1468.31  4871.5 1466.12  4876.8 1466.91  4882.3 1464.80
  4892.9 1463.69  4907.6 1463.87  4933.2 1462.00  4988.2 1460.87  4988.7 1460.37
  5010.5 1460.87  5019.7 1466.90  5060.6 1478.63  5081.0 1486.13  5086.7 1492.61
  5111.7 1503.37  5121.9 1506.79  5136.2 1509.51  5244.6 1511.20  5383.6 1508.45
#Mann=5,-1,0
  4153.3    0.16       0  4329.5   0.035       0  4795.2    0.07       0
  4988.2    0.07       0  5010.5    0.07       0
Bank Sta=4988.2,5010.5
Exp/Cntr=0.3,0.1

Type RM Length L Ch R = 1,7476,713,713,713
BEGIN DESCRIPTION:
Mapping XS fcfd3783
END DESCRIPTION:
XS GIS Cut Line= 3
      1659280.35      7024273.81      1658670.96      7023516.85
      1658417.48      7023134.88
#Sta/Elev= 30
  4031.7 1485.80  4651.6 1474.88  4736.4 1469.60  4794.7 1468.02  4878.7 1465.27
  4913.9 1462.96  4940.0 1459.87  4940.6 1459.78  4957.1 1455.37  4966.7 1454.19
  4967.2 1453.69  4989.1 1454.19  5003.5 1455.32  5006.7 1458.79  5014.0 1460.03
  5027.7 1463.38  5050.1 1466.68  5063.8 1470.52  5078.8 1471.76  5108.9 1480.12
  5122.1 1482.49  5151.0 1496.17  5158.1 1502.44  5166.0 1507.67  5172.0 1508.98
  5194.1 1519.42  5208.1 1521.83  5280.3 1525.05  5374.6 1526.82  5461.9 1529.19
#Mann=9,-1,0
  4031.7   0.035       0  4794.7    0.07       0  4940.0   0.035       0
  4940.6    0.07       0  4966.7    0.07       0  4989.1    0.07       0
  5014.0    0.16       0  5208.1    0.07       0  5374.6   0.035       0
Bank Sta=4966.7,4989.1
Exp/Cntr=0.3,0.1

Type RM Length L Ch R = 1,6763,614,614,614
BEGIN DESCRIPTION:
Mapping XS e341d209
END DESCRIPTION:
XS GIS Cut Line= 3
      1659559.86      7024188.94      1659250.82      7023187.16
      1659139.86      7022835.21
#Sta/Elev= 30
  3949.7 1485.56  4017.9 1484.78  4402.6 1473.37  4502.5 1473.14  4568.1 1472.84
  4683.2 1465.90  4800.5 1462.86  4841.1 1460.77  4860.5 1459.21  4871.6 1456.19
  4892.5 1454.55  4903.7 1456.91  4931.1 1458.76  4976.3 1458.14  4986.7 1457.25
  5007.7 1450.12  5017.4 1449.86  5017.9 1449.36  5039.8 1449.86  5049.6 1462.76
  5081.1 1475.62  5123.0 1488.78  5144.0 1498.10  5172.0 1506.87  5201.0 1512.95
  5265.7 1515.95  5271.0 1517.73  5298.1 1518.75  5303.3 1520.84  5367.1 1524.55
#Mann=7,-1,0
  3949.7   0.035       0  4402.6    0.07       0  4502.5   0.035       0
  4841.1    0.16       0  5017.4    0.07       0  5039.8    0.16       0
  5172.0    0.07       0
Bank Sta=5017.4,5039.8
Exp/Cntr=0.3,0.1

Type RM Length L Ch R = 1,6149,446,446,446
BEGIN DESCRIPTION:
Mapping XS 39512088
END DESCRIPTION:
XS GIS Cut Line= 3
      1659820.27      7024180.20      1659795.96      7023291.33
      1659735.20      7022803.50
#Sta/Elev= 30
  4108.2 1489.97  4160.4 1486.87  4652.3 1473.98  4710.6 1472.66  4800.7 1472.48
  4940.7 1464.91  4950.7 1462.87  4985.3 1447.25  4985.8 1446.75  5007.8 1447.25
  5045.9 1448.83  5061.2 1451.31  5135.4 1454.05  5207.4 1456.44  5234.3 1456.38
  5252.7 1456.99  5272.8 1460.56  5282.9 1463.41  5288.2 1466.05  5303.1 1469.49
  5333.2 1481.08  5363.5 1491.80  5368.9 1496.37  5374.0 1496.50  5403.8 1511.39
  5413.9 1514.80  5444.2 1520.17  5449.7 1521.97  5454.7 1523.38  5489.0 1527.02
#Mann=8,-1,0
  4108.2   0.035       0  4652.3    0.07       0  4985.3    0.07       0
  5007.8    0.07       0  5135.4    0.16       0  5234.3    0.07       0
  5333.2    0.16       0  5449.7    0.07       0
Bank Sta=4985.3,5007.8
Exp/Cntr=0.3,0.1