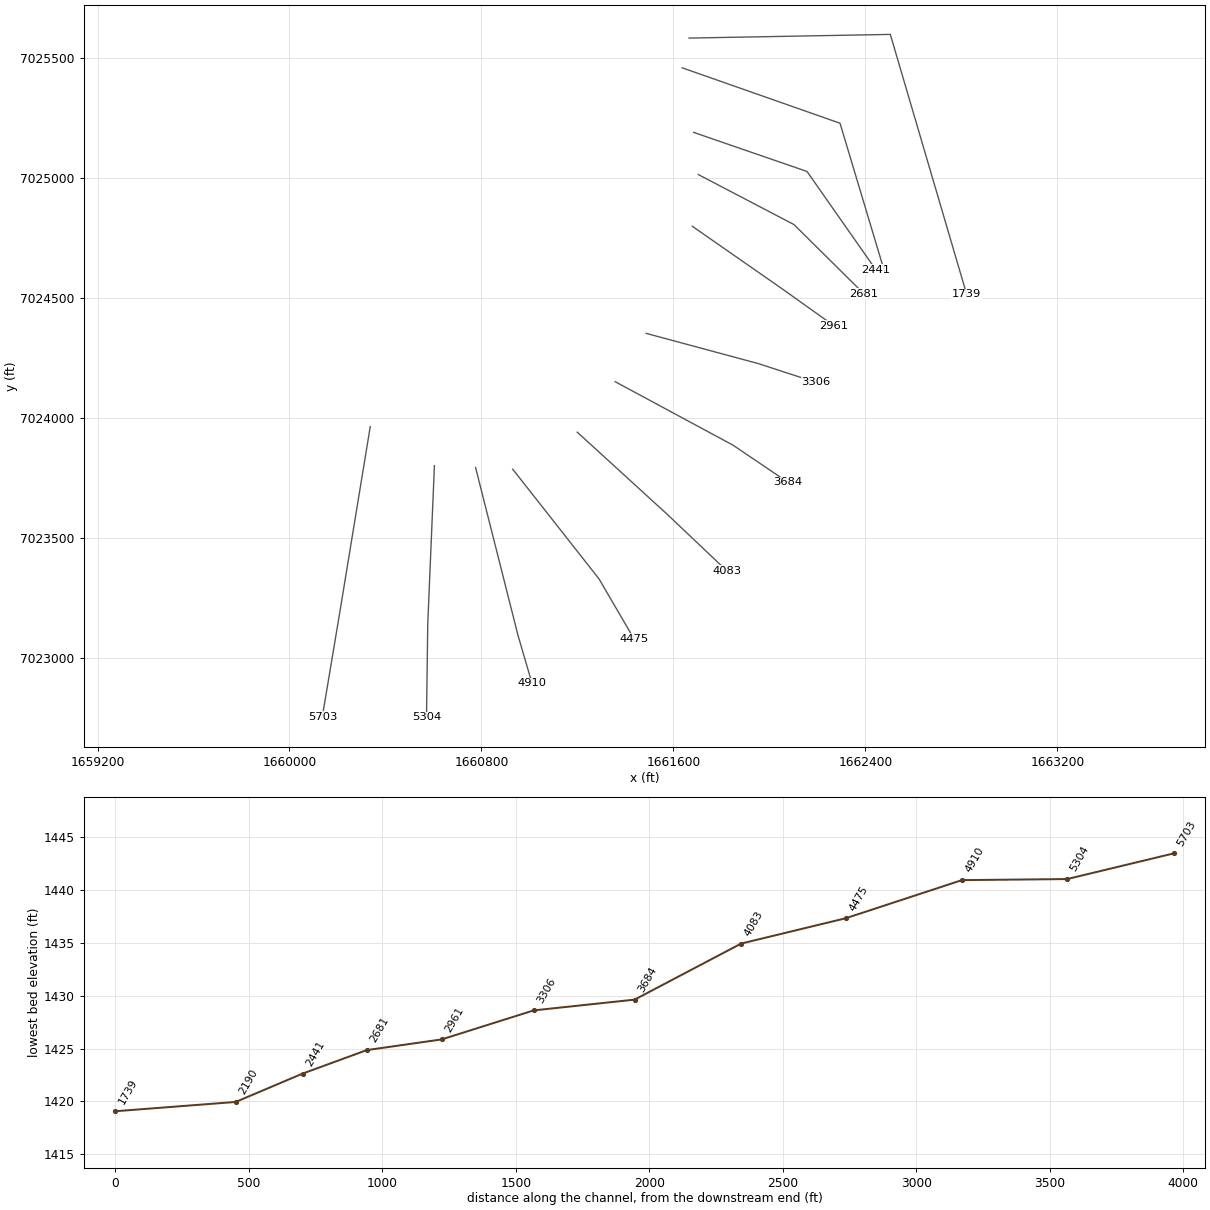
HEC-RAS study Chimney Creek 1174.prj: Chimney Creek 1174 Base Level Engineering

--- Chimney Creek 1174.g01 (geometry) --- (continued)

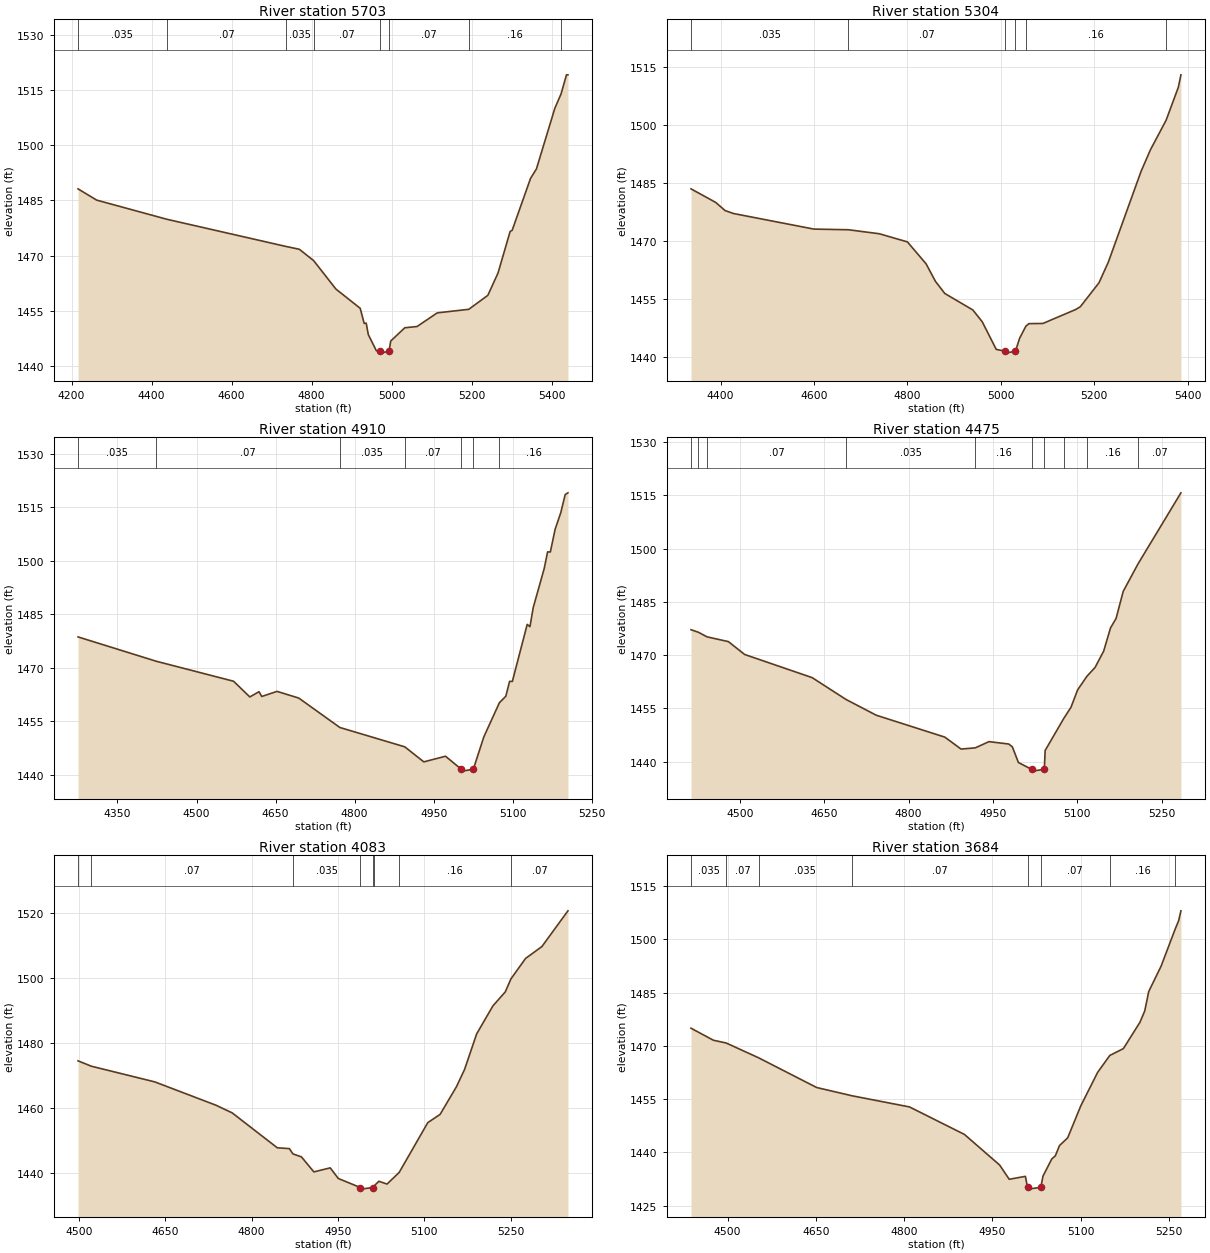
Type RM Length L Ch R = 1,5703,399,399,399
BEGIN DESCRIPTION:
Mapping XS 67911545
END DESCRIPTION:
XS GIS Cut Line= 3
      1660336.58      7023964.05      1660209.85      7023191.50
      1660136.93      7022755.73
#Sta/Elev= 30
  4216.3 1488.13  4263.0 1485.07  4437.9 1479.88  4736.9 1472.46  4769.6 1471.71
  4805.3 1468.63  4860.9 1460.91  4921.7 1455.67  4931.6 1451.57  4936.7 1451.64
  4941.9 1448.53  4962.2 1444.11  4971.2 1443.99  4971.7 1443.49  4993.7 1443.99
  4998.0 1446.78  5033.1 1450.38  5063.7 1450.72  5114.3 1454.43  5193.1 1455.40
  5240.8 1459.20  5266.3 1465.29  5296.5 1476.56  5301.5 1476.86  5347.5 1490.97
  5362.2 1493.55  5408.3 1510.05  5423.8 1513.93  5437.3 1519.12  5441.0 1519.12
#Mann=8,-1,0
  4216.3   0.035       0  4437.9    0.07       0  4736.9   0.035       0
  4805.3    0.07       0  4971.2    0.07       0  4993.7    0.07       0
  5193.1    0.16       0  5423.8    0.07       0
Bank Sta=4971.2,4993.7
Exp/Cntr=0.3,0.1

Type RM Length L Ch R = 1,5304,394,394,394
BEGIN DESCRIPTION:
Mapping XS cadffca2
END DESCRIPTION:
XS GIS Cut Line= 3
      1660603.95      7023800.90      1660576.17      7023141.16
      1660570.97      7022752.62
#Sta/Elev= 30
  4336.8 1483.56  4389.7 1480.05  4409.8 1477.94  4427.7 1477.18  4599.9 1473.15
  4673.8 1472.98  4740.1 1471.94  4800.1 1469.84  4840.1 1464.17  4860.2 1459.62
  4880.2 1456.49  4940.2 1452.23  4960.3 1449.18  4990.3 1442.03  5009.0 1441.56
  5009.5 1441.06  5031.5 1441.56  5040.3 1444.90  5053.8 1448.04  5060.3 1448.69
  5090.3 1448.74  5160.3 1452.34  5170.3 1453.06  5210.3 1459.26  5230.3 1464.61
  5300.3 1488.06  5320.3 1493.64  5354.0 1501.31  5380.3 1509.89  5385.7 1513.06
#Mann=6,-1,0
  4336.8   0.035       0  4673.8    0.07       0  5009.0    0.07       0
  5031.5    0.07       0  5053.8    0.16       0  5354.0    0.07       0
Bank Sta=5009,5031.5
Exp/Cntr=0.3,0.1

Type RM Length L Ch R = 1,4910,435,435,435
BEGIN DESCRIPTION:
Mapping XS d57f30c9
END DESCRIPTION:
XS GIS Cut Line= 3
      1660775.36      7023794.06      1660952.44      7023093.53
      1661010.51      7022894.81
#Sta/Elev= 30
  4275.2 1478.63  4423.4 1471.81  4570.3 1466.19  4601.2 1461.78  4618.6 1463.25
  4623.8 1461.91  4652.8 1463.34  4694.0 1461.47  4772.0 1453.21  4895.2 1447.78
  4931.3 1443.56  4972.5 1445.14  5002.7 1441.46  5003.2 1440.96  5025.2 1441.46
  5045.2 1450.58  5074.8 1460.17  5086.9 1461.97  5094.1 1466.15  5099.3 1466.14
  5127.5 1482.14  5132.7 1481.51  5139.0 1486.90  5159.8 1497.85  5166.2 1502.49
  5171.4 1502.47  5180.6 1508.91  5191.1 1513.45  5199.6 1518.59  5204.8 1519.07
#Mann=7,-1,0
  4275.2   0.035       0  4423.4    0.07       0  4772.0   0.035       0
  4895.2    0.07       0  5002.7    0.07       0  5025.2    0.07       0
  5074.8    0.16       0
Bank Sta=5002.7,5025.2
Exp/Cntr=0.3,0.1

Type RM Length L Ch R = 1,4475,392,392,392
BEGIN DESCRIPTION:
Mapping XS c595be4a
END DESCRIPTION:
XS GIS Cut Line= 3
      1660930.07      7023786.81      1661290.33      7023328.88
      1661435.74      7023079.31
#Sta/Elev= 30
  4413.0 1477.18  4426.1 1476.47  4441.4 1475.18  4479.5 1473.83  4508.4 1470.21
  4628.6 1463.68  4688.6 1457.55  4742.5 1453.10  4864.5 1446.93  4893.4 1443.57
  4918.6 1443.90  4943.1 1445.66  4978.3 1444.98  4984.7 1444.18  4995.4 1439.78
  5018.9 1437.85  5019.4 1437.35  5041.5 1437.85  5043.0 1443.17  5076.3 1452.24
  5088.9 1455.32  5100.8 1460.25  5117.3 1464.07  5131.9 1466.58  5147.1 1471.16
  5159.2 1477.66  5169.1 1480.33  5181.9 1488.00  5208.0 1495.67  5284.5 1515.74
#Mann=10,-1,0
  4413.0    0.07       0  4426.1   0.035       0  4441.4    0.07       0
  4688.6   0.035       0  4918.6    0.16       0  5018.9    0.07       0
  5041.5    0.16       0  5076.3    0.07       0  5117.3    0.16       0
  5208.0    0.07       0
Bank Sta=5018.9,5041.5
Exp/Cntr=0.3,0.1

Type RM Length L Ch R = 1,4083,399,399,399
BEGIN DESCRIPTION:
Mapping XS 665d1196
END DESCRIPTION:
XS GIS Cut Line= 3
      1661199.21      7023940.84      1661572.45      7023600.15
      1661823.34      7023362.24
#Sta/Elev= 30
  4498.4 1474.40  4521.4 1472.76  4631.8 1467.93  4737.8 1460.77  4766.2 1458.40
  4844.6 1447.66  4865.5 1447.41  4871.8 1445.78  4886.5 1444.87  4908.1 1440.25
  4936.5 1441.49  4950.6 1438.22  4988.7 1435.45  4989.2 1434.95  5011.3 1435.45
  5012.5 1435.88  5021.0 1437.37  5035.2 1436.51  5056.3 1440.08  5106.0 1455.40
  5127.4 1457.94  5155.7 1466.41  5169.9 1471.75  5190.9 1482.69  5219.2 1491.32
  5240.7 1495.62  5250.4 1499.60  5275.9 1505.90  5304.2 1509.54  5349.5 1520.54
#Mann=8,-1,0
  4498.4   0.035       0  4521.4    0.07       0  4871.8   0.035       0
  4988.7   0.035       0  5011.3   0.035       0  5012.5    0.07       0
  5056.3    0.16       0  5250.4    0.07       0
Bank Sta=4988.7,5011.3
Exp/Cntr=0.3,0.1

Type RM Length L Ch R = 1,3684,378,378,378
BEGIN DESCRIPTION:
Mapping XS bdac2dd8
END DESCRIPTION:
XS GIS Cut Line= 3
      1661356.98      7024151.36      1661848.51      7023886.61
      1662075.99      7023732.79
#Sta/Elev= 30
  4437.8 1474.95  4475.9 1471.56  4497.5 1470.79  4552.7 1466.62  4651.4 1458.25
  4711.4 1455.93  4809.3 1452.78  4902.6 1445.05  4962.6 1436.41  4978.8 1432.41
  5006.3 1433.24  5009.9 1430.14  5010.4 1429.64  5032.5 1430.14  5036.2 1433.30
  5051.1 1438.13  5057.2 1439.02  5064.3 1441.91  5078.2 1444.09  5100.5 1453.10
  5129.1 1462.51  5149.8 1467.28  5172.9 1469.21  5201.0 1476.61  5209.2 1479.82
  5216.0 1485.29  5237.0 1492.42  5260.9 1502.84  5266.9 1505.25  5270.7 1508.00
#Mann=8,-1,0
  4437.8   0.035       0  4497.5    0.07       0  4552.7   0.035       0
  4711.4    0.07       0  5009.9    0.07       0  5032.5    0.07       0
  5149.8    0.16       0  5260.9    0.07       0
Bank Sta=5009.9,5032.5
Exp/Cntr=0.3,0.1

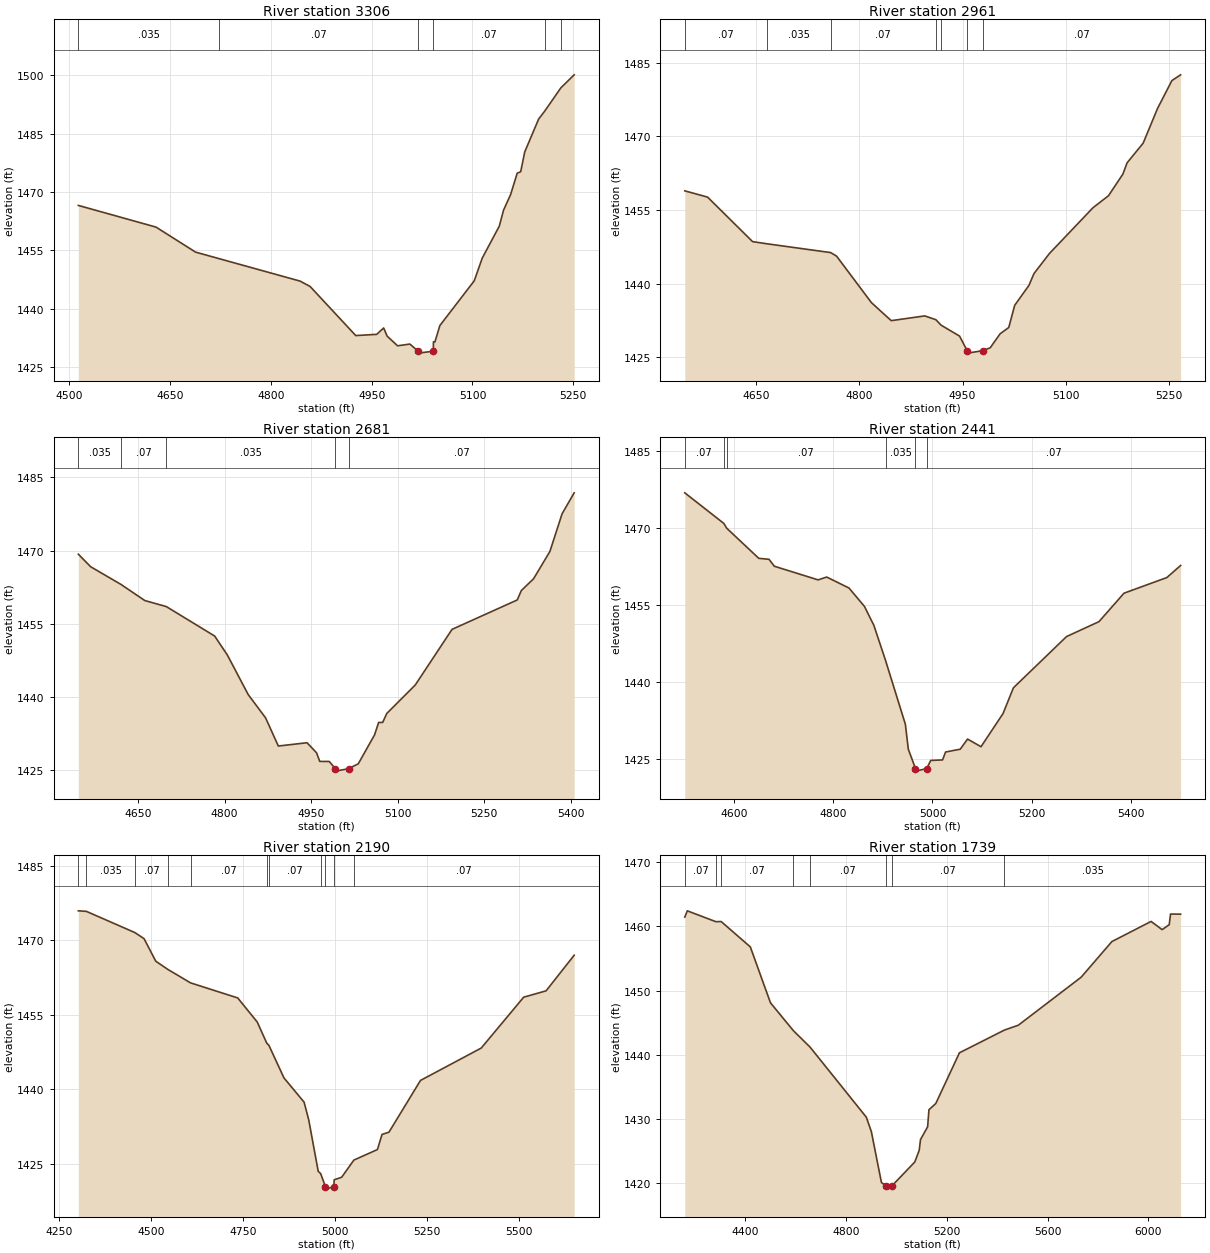
Type RM Length L Ch R = 1,3306,345,345,345
BEGIN DESCRIPTION:
Mapping XS 6daed333
END DESCRIPTION:
XS GIS Cut Line= 3
      1661486.57      7024352.53      1661955.28      7024226.23
      1662194.83      7024148.12
#Sta/Elev= 30
  4513.8 1466.56  4629.3 1460.99  4688.2 1454.56  4723.7 1452.86  4843.6 1447.12
  4858.5 1445.74  4926.4 1433.13  4957.5 1433.44  4967.9 1435.08  4973.1 1432.98
  4988.6 1430.50  5006.9 1430.95  5019.2 1429.12  5019.7 1428.62  5041.8 1429.12
  5041.9 1431.52  5044.1 1431.48  5051.5 1435.71  5102.6 1447.19  5114.6 1453.06
  5139.8 1461.21  5146.2 1465.35  5156.7 1469.35  5166.5 1474.84  5171.7 1475.21
  5177.7 1480.30  5198.4 1488.74  5207.1 1490.70  5231.5 1496.77  5251.2 1500.10
#Mann=6,-1,0
  4513.8   0.035       0  4723.7    0.07       0  5019.2    0.07       0
  5041.8    0.07       0  5207.1    0.16       0  5231.5    0.07       0
Bank Sta=5019.2,5041.8
Exp/Cntr=0.3,0.1

Type RM Length L Ch R = 1,2961,280,280,280
BEGIN DESCRIPTION:
Mapping XS 8c4f9123
END DESCRIPTION:
XS GIS Cut Line= 3
      1661678.50      7024798.97      1662049.59      7024540.72
      1662268.79      7024384.46
#Sta/Elev= 30
  4545.9 1458.91  4579.1 1457.63  4644.5 1448.57  4665.0 1448.14  4758.1 1446.34
  4766.7 1445.62  4817.4 1436.15  4846.2 1432.48  4895.0 1433.45  4911.2 1432.67
  4918.9 1431.55  4945.6 1429.34  4956.7 1426.37  4957.2 1425.87  4979.4 1426.37
  4990.2 1426.96  5004.7 1429.82  5017.2 1431.09  5025.8 1435.60  5046.7 1439.70
  5053.8 1442.05  5076.2 1446.13  5139.7 1455.47  5162.3 1457.92  5183.2 1462.32
  5189.3 1464.61  5212.7 1468.62  5233.6 1475.68  5254.5 1481.36  5267.2 1482.53
#Mann=7,-1,0
  4545.9    0.07       0  4665.0   0.035       0  4758.1    0.07       0
  4911.2   0.035       0  4918.9    0.07       0  4956.7    0.07       0
  4979.4    0.07       0
Bank Sta=4956.7,4979.4
Exp/Cntr=0.3,0.1

Type RM Length L Ch R = 1,2681,240,240,240
BEGIN DESCRIPTION:
Mapping XS 8d9d0286
END DESCRIPTION:
XS GIS Cut Line= 3
      1661703.82      7025014.34      1662102.47      7024805.91
      1662393.95      7024517.36
#Sta/Elev= 30
  4546.2 1469.27  4567.6 1466.70  4620.2 1463.08  4661.5 1459.78  4698.9 1458.54
  4782.7 1452.51  4804.8 1448.61  4840.9 1440.52  4871.0 1435.77  4893.1 1430.00
  4942.9 1430.67  4959.3 1428.63  4965.0 1426.85  4981.4 1426.84  4992.1 1425.36
  4992.6 1424.86  5014.8 1425.36  5031.7 1426.35  5060.0 1432.28  5067.1 1434.83
  5074.1 1434.83  5081.2 1436.67  5130.7 1442.51  5194.4 1453.88  5307.5 1459.90
  5314.6 1461.83  5335.8 1464.24  5364.1 1469.82  5385.3 1477.55  5406.2 1481.83
#Mann=5,-1,0
  4546.2   0.035       0  4620.2    0.07       0  4698.9   0.035       0
  4992.1    0.07       0  5014.8    0.07       0
Bank Sta=4992.1,5014.8
Exp/Cntr=0.3,0.1

Type RM Length L Ch R = 1,2441,251,251,251
BEGIN DESCRIPTION:
Mapping XS 8aa4c6f7
END DESCRIPTION:
XS GIS Cut Line= 3
      1661684.32      7025190.11      1662156.65      7025027.32
      1662443.86      7024617.18
#Sta/Elev= 30
  4500.4 1476.80  4579.1 1470.85  4585.0 1469.91  4649.7 1464.05  4670.4 1463.86
  4680.9 1462.52  4769.3 1459.86  4786.7 1460.41  4831.7 1458.27  4862.9 1454.69
  4881.9 1451.00  4905.4 1444.18  4945.4 1431.76  4951.3 1426.92  4965.8 1423.14
  4966.3 1422.64  4988.5 1423.14  4996.5 1424.72  5020.4 1424.82  5026.5 1426.36
  5056.1 1426.91  5070.9 1428.88  5098.0 1427.39  5142.4 1433.84  5163.4 1438.86
  5270.6 1448.83  5336.0 1451.73  5386.5 1457.27  5472.9 1460.31  5500.7 1462.66
#Mann=6,-1,0
  4500.4    0.07       0  4579.1   0.035       0  4585.0    0.07       0
  4905.4   0.035       0  4965.8    0.07       0  4988.5    0.07       0
Bank Sta=4965.8,4988.5
Exp/Cntr=0.3,0.1

Type RM Length L Ch R = 1,2190,451,451,451
BEGIN DESCRIPTION:
Mapping XS c1a37465
END DESCRIPTION:
XS GIS Cut Line= 3
      1661636.57      7025459.21      1662294.21      7025228.33
      1662480.76      7024606.30
#Sta/Elev= 30
  4303.0 1475.92  4324.9 1475.81  4456.7 1471.54  4481.5 1470.32  4513.3 1465.79
  4545.8 1464.15  4607.8 1461.43  4735.9 1458.40  4788.9 1453.55  4814.6 1449.32
  4820.4 1448.88  4861.4 1442.32  4916.0 1437.45  4928.7 1433.87  4954.4 1423.54
  4961.0 1423.07  4974.1 1420.45  4974.6 1419.95  4996.8 1420.45  4997.8 1421.83
  5018.1 1422.34  5051.2 1425.79  5115.2 1427.91  5127.7 1430.95  5146.5 1431.40
  5232.1 1441.81  5397.1 1448.32  5512.3 1458.55  5573.2 1459.83  5649.4 1466.99
#Mann=11,-1,0
  4303.0    0.07       0  4324.9   0.035       0  4456.7    0.07       0
  4545.8   0.035       0  4607.8    0.07       0  4814.6   0.035       0
  4820.4    0.07       0  4961.0   0.035       0  4974.1   0.035       0
  4996.8   0.035       0  5051.2    0.07       0
Bank Sta=4974.1,4996.8
Exp/Cntr=0.3,0.1

Type RM Length L Ch R = 1,1739,0,0,0
BEGIN DESCRIPTION:
Mapping XS 0bd38036
END DESCRIPTION:
XS GIS Cut Line= 3
      1661665.14      7025583.14      1662503.79      7025598.48
      1662821.75      7024516.33
#Sta/Elev= 30
  4161.2 1461.45  4171.1 1462.43  4284.3 1460.74  4305.5 1460.76  4421.1 1456.81
  4501.1 1448.10  4591.6 1443.77  4657.6 1441.22  4881.2 1430.28  4901.2 1428.03
  4941.2 1420.10  4959.9 1419.57  4960.4 1419.07  4982.6 1419.57  5073.5 1423.30
  5091.0 1425.12  5096.2 1426.79  5124.4 1428.78  5129.6 1431.44  5156.8 1432.41
  5250.6 1440.31  5429.0 1443.85  5484.2 1444.61  5733.4 1452.09  5855.2 1457.64
  6010.8 1460.78  6054.6 1459.50  6082.7 1460.27  6087.9 1461.93  6127.9 1461.91
#Mann=8,-1,0
  4161.2    0.07       0  4284.3   0.035       0  4305.5    0.07       0
  4591.6   0.035       0  4657.6    0.07       0  4959.9    0.07       0
  4982.6    0.07       0  5429.0   0.035       0
Bank Sta=4959.9,4982.6
Exp/Cntr=0.3,0.1

Chan Stop Cuts=-1