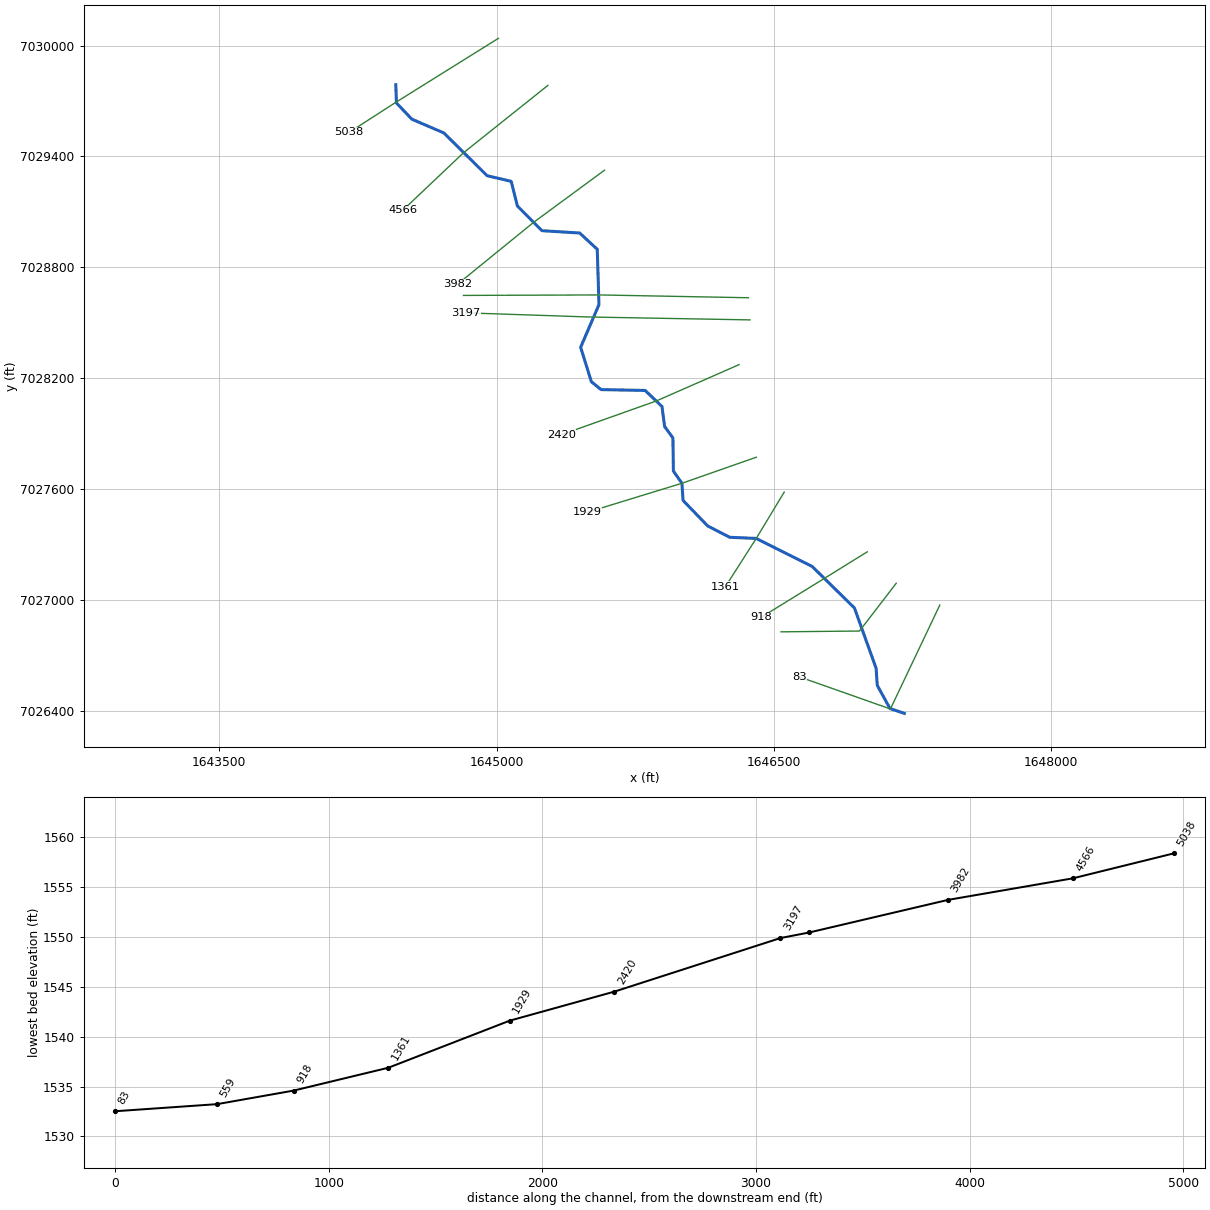
--- Chimney Creek 1175.prj (project) ---

Proj Title=Chimney Creek 1175 Base Level Engineering
Current Plan=p01
Default Exp/Contr=0.3,0.1
English Units
Geom File=g01
Flow File=f01
Plan File=p01
BEGIN DESCRIPTION:
Chimney Creek 1175
END DESCRIPTION:

--- Chimney Creek 1175.p01 (plan) ---

Plan Title=Multiple Run
Short Identifier=Multiple
Geom File=g01
Flow File=f01
Subcritical Flow
K Sum by GR= 0
Std Step Tol= 0.01
Critical Tol= 0.01
Num of Std Step Trials= 20
Max Error Tol= 0.3
Flow Tol Ratio= 0.001
Split Flow NTrial= 30
Split Flow Tol= 0.02
Split Flow Ratio= 0.02
Log Output Level= 0
Friction Slope Method= 1
Unsteady Friction Slope Method= 2
Unsteady Bridges Friction Slope Method= 1
Parabolic Critical Depth
Global Vel Dist=  1 , 1 , 1
Global Log Level= 0
CheckData=True
Encroach Param= -1, 0, 0, 0
BEGIN DESCRIPTION:
Multiple Run
END DESCRIPTION:

--- Chimney Creek 1175.f01 (steady flow) ---

Flow Title=Multiple
Number of Profiles=7
Profile Names=10-year,25-year,50-year,1pct_min,100-year,1pct_plu,500-year
River Rch & RM= Chimney Creek 11,Reach-1,5038
     296     410     505     309     617    1231     933
Boundary for River Rch & Prof#=Chimney Creek 11,Reach-1,1
Up Type=0
Dn Type=3
Dn Slope=0.005
Boundary for River Rch & Prof#=Chimney Creek 11,Reach-1,2
Up Type=0
Dn Type=3
Dn Slope=0.005
Boundary for River Rch & Prof#=Chimney Creek 11,Reach-1,3
Up Type=0
Dn Type=3
Dn Slope=0.005
Boundary for River Rch & Prof#=Chimney Creek 11,Reach-1,4
Up Type=0
Dn Type=3
Dn Slope=0.005
Boundary for River Rch & Prof#=Chimney Creek 11,Reach-1,5
Up Type=0
Dn Type=3
Dn Slope=0.005
Boundary for River Rch & Prof#=Chimney Creek 11,Reach-1,6
Up Type=0
Dn Type=3
Dn Slope=0.005
Boundary for River Rch & Prof#=Chimney Creek 11,Reach-1,7
Up Type=0
Dn Type=3
Dn Slope=0.005

--- Chimney Creek 1175.g01 (geometry) ---

Geom Title=Existing Conditions

River Reach=Chimney Creek 11,Reach-1
Reach XY= 30
      1644455.00      7029788.00      1644458.38      7029689.39
      1644541.76      7029601.61      1644714.68      7029527.24
      1644948.83      7029295.86      1645079.01      7029265.33
      1645112.86      7029131.83      1645245.20      7028998.48
      1645449.57      7028985.83      1645544.53      7028897.83
      1645553.78      7028598.50      1645454.72      7028367.82
      1645512.72      7028181.50      1645565.26      7028138.98
      1645803.55      7028134.47      1645894.49      7028047.81
      1645908.86      7027939.60      1645953.78      7027877.50
      1645956.22      7027698.50      1646002.53      7027632.43
      1646008.61      7027539.50      1646141.78      7027401.62
      1646260.93      7027340.25      1646403.44      7027334.24
      1646707.30      7027182.17      1646935.37      7026958.16
      1647052.65      7026632.03      1647058.82      7026539.58
      1647127.72      7026414.15      1647205.00      7026388.00

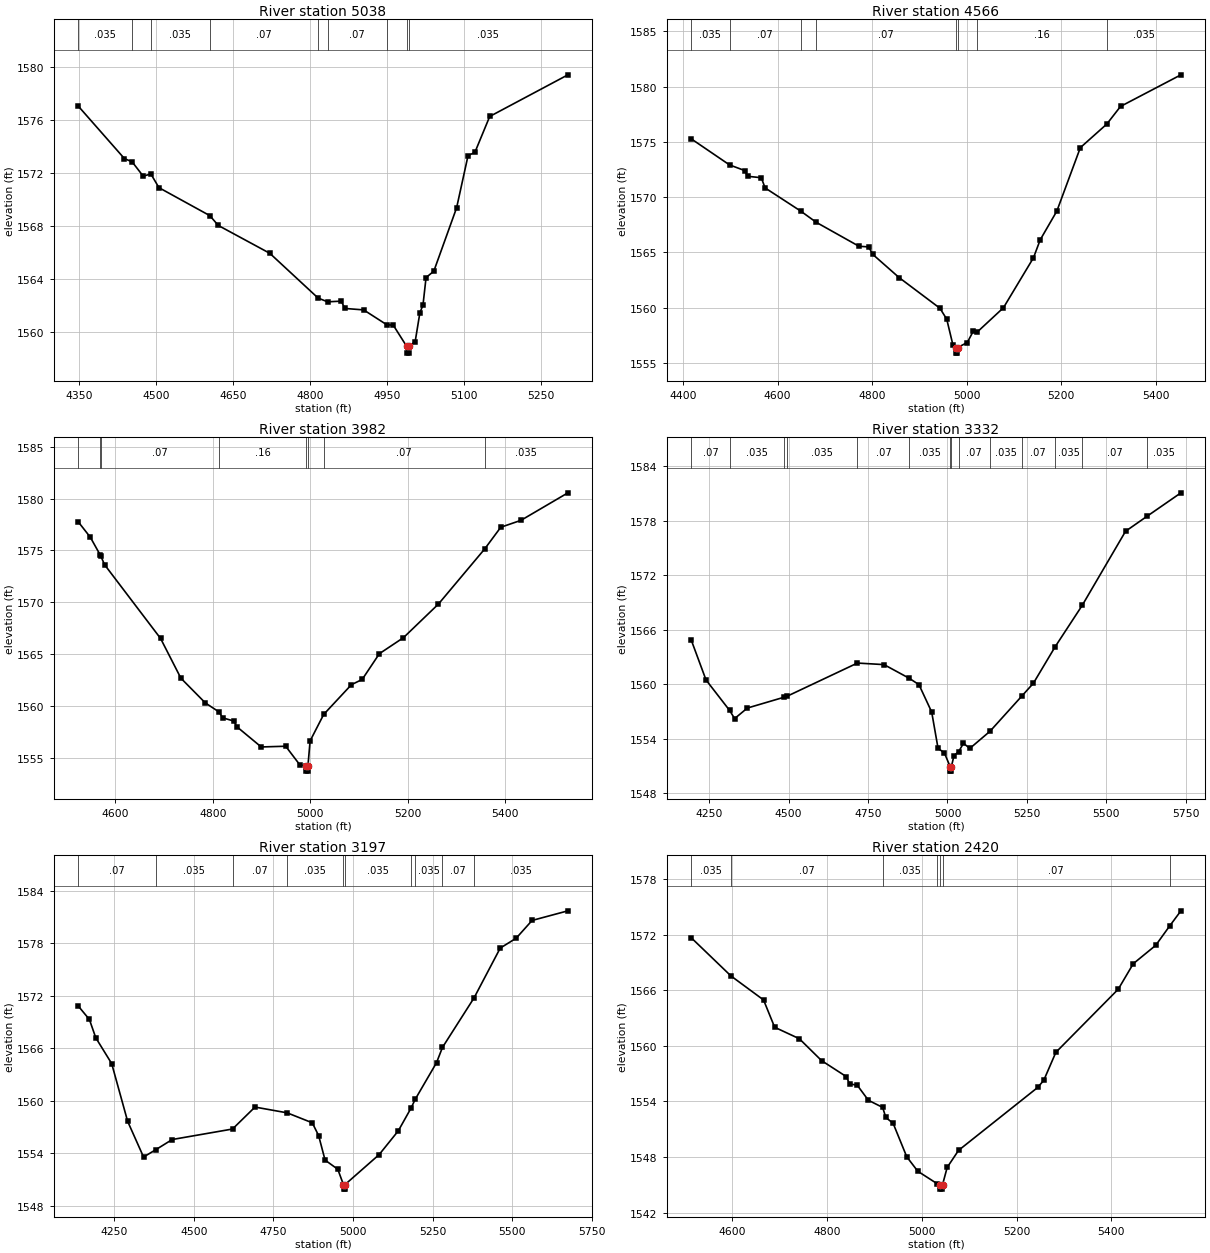
Type RM Length L Ch R = 1,5038,472,472,472
BEGIN DESCRIPTION:
Chimney Creek 1175 10.0
END DESCRIPTION:
XS GIS Cut Line= 3
      1645009.98      7030038.75      1644456.85      7029693.76
      1644202.70      7029530.08
#Sta/Elev= 30
  4348.1 1577.04  4438.5 1573.06  4453.4 1572.82  4475.0 1571.74  4490.0 1571.90
  4505.7 1570.87  4604.8 1568.76  4621.3 1568.02  4721.6 1565.92  4815.8 1562.54
  4834.3 1562.26  4860.8 1562.31  4867.9 1561.76  4904.5 1561.65  4949.1 1560.54
  4962.3 1560.49  4988.4 1558.89  4988.6 1558.39  4992.1 1558.39  4992.4 1558.89
  5004.8 1559.26  5014.0 1561.44  5020.0 1562.01  5026.0 1564.09  5041.1 1564.57
  5085.5 1569.35  5107.8 1573.29  5121.1 1573.53  5150.0 1576.24  5302.3 1579.38
#Mann=9,-1,0
  4348.1   0.035       0  4453.4    0.07       0  4490.0   0.035       0
  4604.8    0.07       0  4815.8   0.035       0  4834.3    0.07       0
  4949.1   0.035       0  4988.4   0.035       0  4992.4   0.035       0
Bank Sta=4988.4,4992.4
Exp/Cntr=0.3,0.1

Type RM Length L Ch R = 1,4566,584,584,584
BEGIN DESCRIPTION:
Mapping XS 3b467aee
END DESCRIPTION:
XS GIS Cut Line= 3
      1645277.76      7029784.46      1644821.13      7029419.85
      1644492.98      7029109.06
#Sta/Elev= 30
  4417.1 1575.29  4498.5 1572.92  4530.5 1572.41  4536.9 1571.89  4565.7 1571.76
  4573.7 1570.84  4648.8 1568.75  4681.8 1567.73  4772.3 1565.56  4793.1 1565.50
  4801.1 1564.84  4857.1 1562.73  4943.6 1559.95  4958.0 1558.96  4970.9 1556.66
  4976.8 1556.39  4977.1 1555.89  4980.6 1555.89  4980.8 1556.39  5001.4 1556.85
  5014.1 1557.87  5022.8 1557.81  5078.0 1560.00  5141.5 1564.52  5155.7 1566.14
  5190.9 1568.74  5240.6 1574.48  5296.7 1576.62  5325.6 1578.21  5453.4 1581.07
#Mann=8,-1,0
  4417.1   0.035       0  4498.5    0.07       0  4648.8   0.035       0
  4681.8    0.07       0  4976.8    0.07       0  4980.8    0.07       0
  5022.8    0.16       0  5296.7   0.035       0
Bank Sta=4976.8,4980.8
Exp/Cntr=0.3,0.1

Type RM Length L Ch R = 1,3982,650,650,650
BEGIN DESCRIPTION:
Mapping XS 85175966
END DESCRIPTION:
XS GIS Cut Line= 3
      1645583.65      7029325.52      1645199.56      7029042.99
      1644789.09      7028709.15
#Sta/Elev= 30
  4523.3 1577.79  4548.5 1576.28  4569.3 1574.53  4569.8 1574.49  4577.8 1573.63
  4692.8 1566.52  4734.5 1562.69  4784.6 1560.31  4813.3 1559.42  4820.1 1558.87
  4843.2 1558.56  4849.4 1558.01  4899.5 1556.06  4949.7 1556.13  4979.0 1554.32
  4991.3 1554.23  4991.6 1553.73  4995.2 1553.73  4995.4 1554.23  4999.8 1556.64
  5027.8 1559.20  5084.6 1562.06  5106.8 1562.57  5142.0 1565.05  5191.6 1566.60
  5263.4 1569.84  5358.5 1575.16  5391.3 1577.24  5432.9 1577.91  5529.2 1580.56
#Mann=8,-1,0
  4523.3    0.07       0  4569.3   0.035       0  4569.8    0.07       0
  4813.3    0.16       0  4991.3    0.07       0  4995.4    0.16       0
  5027.8    0.07       0  5358.5   0.035       0
Bank Sta=4991.3,4995.4
Exp/Cntr=0.3,0.1

Type RM Length L Ch R = 1,3332,135,135,135
BEGIN DESCRIPTION:
Mapping XS a658fa6f
END DESCRIPTION:
XS GIS Cut Line= 3
      1646362.07      7028635.79      1645555.31      7028650.99
      1644820.82      7028648.38
#Sta/Elev= 30
  4193.1 1564.94  4240.2 1560.49  4314.4 1557.14  4330.2 1556.24  4370.2 1557.40
  4484.7 1558.58  4494.7 1558.69  4716.5 1562.35  4800.3 1562.18  4880.4 1560.66
  4910.3 1559.97  4950.3 1556.96  4970.3 1552.97  4990.3 1552.46  5008.2 1550.96
  5008.5 1550.46  5012.1 1550.46  5012.4 1550.96  5020.3 1552.16  5034.8 1552.59
  5050.3 1553.52  5070.3 1552.96  5133.9 1554.85  5232.9 1558.68  5270.3 1560.13
  5338.5 1564.13  5423.8 1568.69  5560.3 1576.85  5629.1 1578.53  5734.5 1581.08
#Mann=14,-1,0
  4193.1    0.07       0  4314.4   0.035       0  4484.7    0.07       0
  4494.7   0.035       0  4716.5    0.07       0  4880.4   0.035       0
  5008.2   0.035       0  5012.4   0.035       0  5034.8    0.07       0
  5133.9   0.035       0  5232.9    0.07       0  5338.5   0.035       0
  5423.8    0.07       0  5629.1   0.035       0
Bank Sta=5008.2,5012.4
Exp/Cntr=0.3,0.1

Type RM Length L Ch R = 1,3197,777,777,777
BEGIN DESCRIPTION:
Mapping XS c5be1a1a
END DESCRIPTION:
XS GIS Cut Line= 3
      1646370.73      7028516.00      1645504.44      7028531.62
      1644832.55      7028554.19
#Sta/Elev= 30
  4136.4 1570.86  4172.1 1569.29  4192.1 1567.20  4242.1 1564.25  4292.2 1557.65
  4342.2 1553.57  4379.9 1554.39  4432.2 1555.57  4621.7 1556.77  4692.2 1559.28
  4793.3 1558.62  4872.2 1557.48  4892.2 1556.01  4912.3 1553.22  4952.3 1552.17
  4970.2 1550.40  4970.4 1549.90  4974.1 1549.90  4974.4 1550.40  5082.3 1553.85
  5142.3 1556.56  5181.9 1559.13  5195.7 1560.18  5262.4 1564.35  5281.1 1566.10
  5380.3 1571.76  5462.5 1577.45  5512.6 1578.58  5562.6 1580.61  5675.1 1581.71
#Mann=10,-1,0
  4136.4    0.07       0  4379.9   0.035       0  4621.7    0.07       0
  4793.3   0.035       0  4970.2   0.035       0  4974.4   0.035       0
  5181.9    0.07       0  5195.7   0.035       0  5281.1    0.07       0
  5380.3   0.035       0
Bank Sta=4970.2,4974.4
Exp/Cntr=0.3,0.1

Type RM Length L Ch R = 1,2420,491,491,491
BEGIN DESCRIPTION:
Mapping XS 9bb1c08c
END DESCRIPTION:
XS GIS Cut Line= 3
      1646311.32      7028273.96      1645863.36      7028077.33
      1645350.31      7027895.02
#Sta/Elev= 30
  4513.1 1571.71  4597.4 1567.56  4666.1 1564.97  4689.5 1562.02  4741.6 1560.78
  4788.4 1558.42  4840.6 1556.69  4847.6 1555.91  4863.9 1555.75  4887.3 1554.13
  4917.4 1553.36  4924.1 1552.27  4939.5 1551.64  4968.3 1548.02  4991.6 1546.46
  5032.3 1545.12  5038.9 1545.03  5039.3 1544.53  5043.5 1544.53  5043.9 1545.03
  5053.6 1546.88  5077.6 1548.72  5244.7 1555.52  5257.4 1556.29  5282.9 1559.31
  5414.5 1566.13  5446.3 1568.89  5493.6 1570.87  5522.7 1572.94  5546.8 1574.60
#Mann=7,-1,0
  4513.1   0.035       0  4597.4    0.07       0  4917.4   0.035       0
  5032.3    0.07       0  5038.9   0.035       0  5043.9    0.07       0
  5522.7   0.035       0
Bank Sta=5038.9,5043.9
Exp/Cntr=0.3,0.1

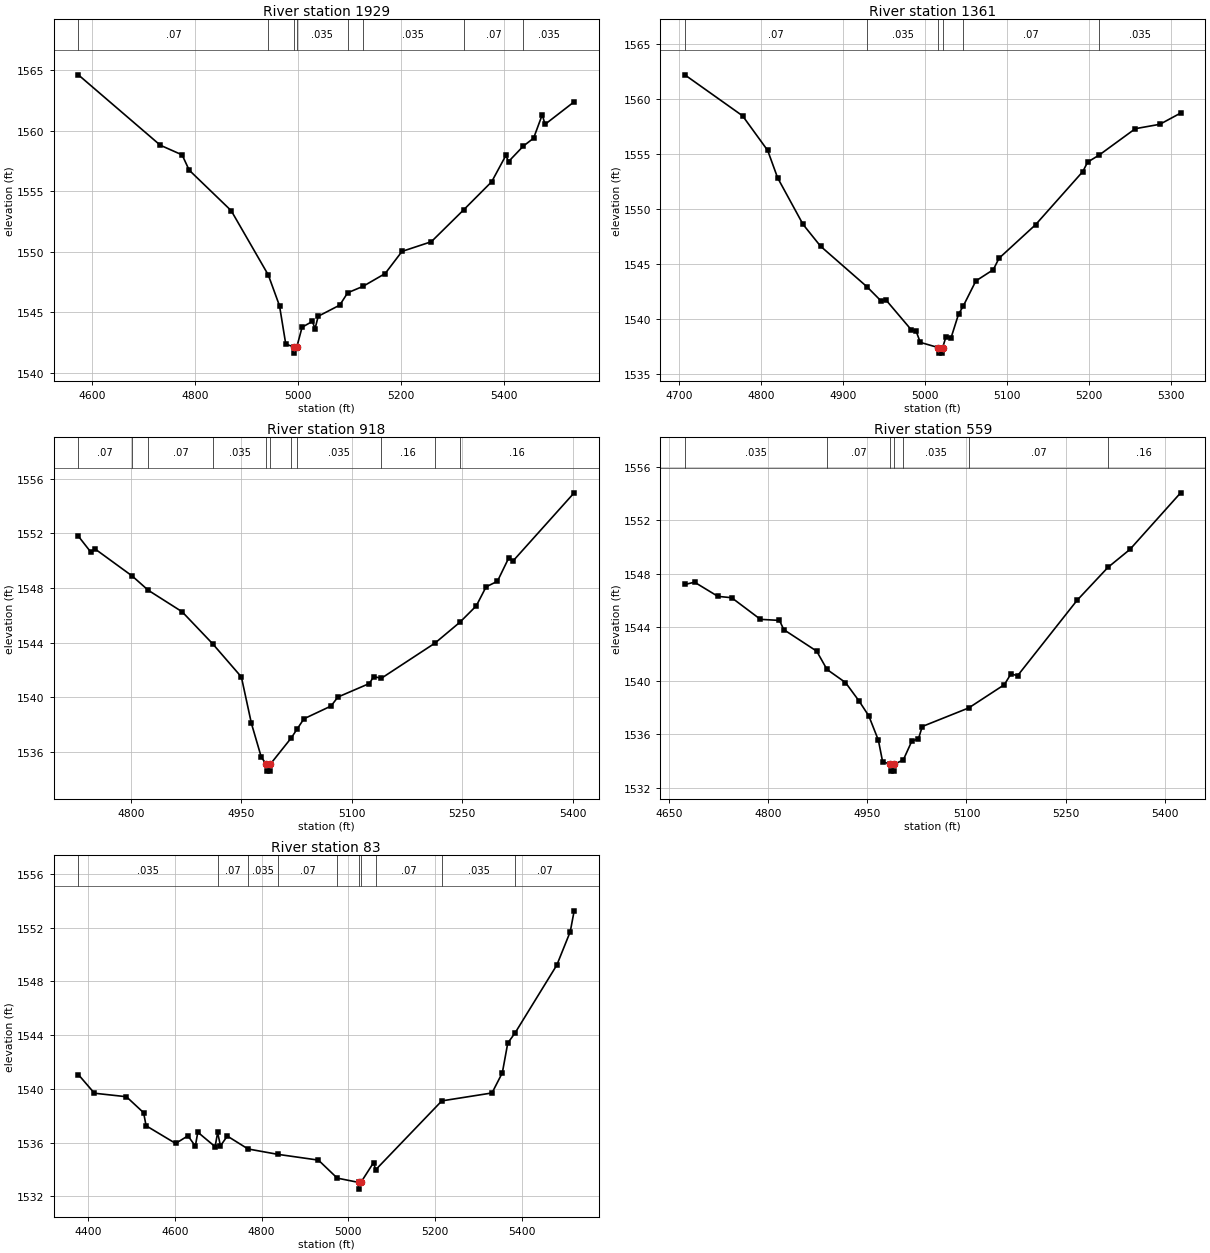
Type RM Length L Ch R = 1,1929,568,568,568
BEGIN DESCRIPTION:
Mapping XS 450949c8
END DESCRIPTION:
XS GIS Cut Line= 3
      1646405.23      7027773.50      1646002.69      7027632.45
      1645489.69      7027475.19
#Sta/Elev= 30
  4573.3 1564.62  4732.5 1558.80  4774.9 1558.00  4788.6 1556.74  4870.2 1553.39
  4942.3 1548.07  4964.1 1545.52  4976.2 1542.36  4992.6 1542.11  4993.0 1541.61
  4997.6 1542.11  5007.9 1543.75  5027.8 1544.23  5033.1 1543.64  5039.3 1544.66
  5081.1 1545.58  5096.5 1546.60  5126.2 1547.13  5169.3 1548.19  5202.0 1550.02
  5258.9 1550.82  5321.6 1553.45  5376.2 1555.78  5403.7 1557.95  5409.0 1557.45
  5437.7 1558.73  5457.6 1559.38  5474.5 1561.33  5479.7 1560.52  5536.4 1562.39
#Mann=8,-1,0
  4573.3    0.07       0  4942.3   0.035       0  4992.6   0.035       0
  4997.6   0.035       0  5096.5    0.07       0  5126.2   0.035       0
  5321.6    0.07       0  5437.7   0.035       0
Bank Sta=4992.6,4997.6
Exp/Cntr=0.3,0.1

Type RM Length L Ch R = 1,1361,443,443,443
BEGIN DESCRIPTION:
Mapping XS 8af0013f
END DESCRIPTION:
XS GIS Cut Line= 3
      1646555.63      7027584.46      1646404.79      7027334.87
      1646236.42      7027071.52
#Sta/Elev= 30
  4707.2 1562.21  4777.6 1558.48  4808.2 1555.33  4820.3 1552.84  4851.3 1548.60
  4872.6 1546.62  4929.3 1542.92  4946.3 1541.64  4952.2 1541.74  4983.2 1539.01
  4989.0 1538.91  4994.1 1537.87  5016.3 1537.39  5016.7 1536.89  5021.0 1536.89
  5021.4 1537.39  5025.5 1538.39  5031.5 1538.25  5040.8 1540.44  5046.3 1541.14
  5061.9 1543.46  5083.1 1544.48  5090.1 1545.52  5134.6 1548.57  5192.2 1553.41
  5198.1 1554.27  5212.5 1554.93  5256.2 1557.31  5286.1 1557.71  5311.4 1558.73
#Mann=6,-1,0
  4707.2    0.07       0  4929.3   0.035       0  5016.3   0.035       0
  5021.4   0.035       0  5046.3    0.07       0  5212.5   0.035       0
Bank Sta=5016.3,5021.4
Exp/Cntr=0.3,0.1

Type RM Length L Ch R = 1,918,359,359,359
BEGIN DESCRIPTION:
Mapping XS 748c03c2
END DESCRIPTION:
XS GIS Cut Line= 3
      1647004.77      7027261.74      1646773.65      7027118.51
      1646431.87      7026908.02
#Sta/Elev= 30
  4728.8 1551.79  4745.8 1550.62  4752.1 1550.83  4801.8 1548.88  4823.8 1547.83
  4869.7 1546.26  4911.3 1543.91  4950.2 1541.49  4963.8 1538.10  4977.3 1535.61
  4984.2 1535.10  4984.6 1534.60  4989.0 1534.60  4989.4 1535.10  5018.1 1537.04
  5025.9 1537.68  5035.2 1538.43  5071.9 1539.36  5081.3 1540.02  5124.0 1541.01
  5129.9 1541.52  5140.2 1541.39  5213.2 1543.97  5246.9 1545.49  5269.2 1546.69
  5282.5 1548.08  5297.9 1548.49  5313.3 1550.20  5319.2 1549.98  5402.1 1554.96
#Mann=11,-1,0
  4728.8    0.07       0  4801.8   0.035       0  4823.8    0.07       0
  4911.3   0.035       0  4984.2   0.035       0  4989.4   0.035       0
  5018.1    0.07       0  5025.9   0.035       0  5140.2    0.16       0
  5213.2    0.07       0  5246.9    0.16       0
Bank Sta=4984.2,4989.4
Exp/Cntr=0.3,0.1

Type RM Length L Ch R = 1,559,476,476,476
BEGIN DESCRIPTION:
Mapping XS 03f22335
END DESCRIPTION:
XS GIS Cut Line= 3
      1647161.40      7027091.63      1646962.81      7026833.35
      1646538.23      7026829.03
#Sta/Elev= 30
  4673.7 1547.21  4688.5 1547.38  4723.8 1546.32  4744.6 1546.22  4788.2 1544.60
  4817.0 1544.52  4823.5 1543.83  4873.3 1542.22  4888.9 1540.85  4916.9 1539.87
  4937.7 1538.47  4952.2 1537.37  4966.7 1535.55  4973.0 1533.96  4984.9 1533.74
  4985.3 1533.24  4989.7 1533.24  4990.1 1533.74  5004.4 1534.08  5017.3 1535.49
  5027.3 1535.66  5033.1 1536.58  5103.4 1537.97  5157.3 1539.71  5167.3 1540.52
  5177.3 1540.38  5267.3 1546.02  5314.1 1548.49  5347.3 1549.83  5424.1 1554.07
#Mann=7,-1,0
  4673.7   0.035       0  4888.9    0.07       0  4984.9    0.07       0
  4990.1    0.07       0  5004.4   0.035       0  5103.4    0.07       0
  5314.1    0.16       0
Bank Sta=4984.9,4990.1
Exp/Cntr=0.3,0.1

Type RM Length L Ch R = 1,83,0,0,0
BEGIN DESCRIPTION:
Chimney Creek 1175 1.0
END DESCRIPTION:
XS GIS Cut Line= 3
      1647397.18      7026973.90      1647130.00      7026411.88
      1646638.84      7026585.06
#Sta/Elev= 30
  4377.7 1541.06  4414.8 1539.67  4488.5 1539.41  4528.2 1538.22  4533.9 1537.25
  4602.1 1535.93  4630.4 1536.50  4647.5 1535.73  4653.1 1536.77  4693.0 1535.69
  4698.9 1536.75  4705.3 1535.75  4721.2 1536.48  4768.9 1535.52  4837.6 1535.12
  4931.2 1534.69  4974.6 1533.35  5023.9 1533.03  5024.3 1532.53  5029.1 1533.03
  5058.3 1534.50  5063.2 1533.97  5215.7 1539.10  5331.4 1539.69  5355.2 1541.19
  5367.7 1543.40  5385.0 1544.18  5480.8 1549.21  5511.8 1551.70  5520.8 1553.25
#Mann=10,-1,0
  4377.7   0.035       0  4698.9    0.07       0  4768.9   0.035       0
  4837.6    0.07       0  4974.6   0.033       0  5023.9   0.033       0
  5029.1   0.033       0  5063.2    0.07       0  5215.7   0.035       0
  5385.0    0.07       0
Bank Sta=5023.9,5029.1
Exp/Cntr=0.3,0.1

Chan Stop Cuts=-1