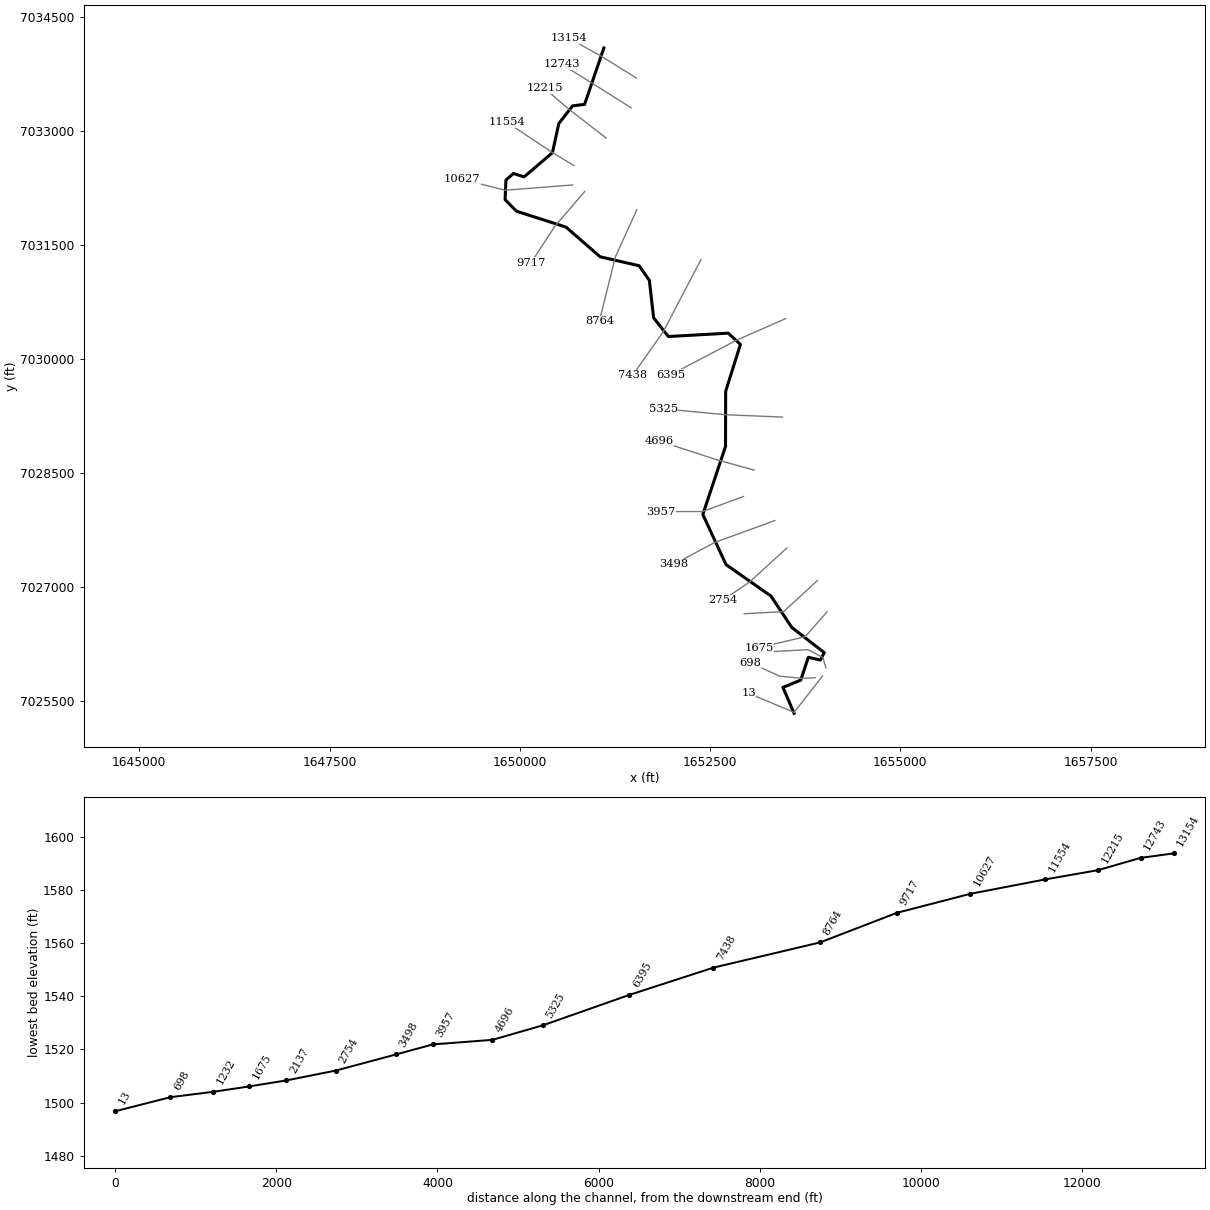
--- Chimney Creek 1176.prj (project) ---

Proj Title=Chimney Creek 1176 Base Level Engineering
Current Plan=p01
Default Exp/Contr=0.3,0.1
English Units
Geom File=g01
Flow File=f01
Plan File=p01
BEGIN DESCRIPTION:
Chimney Creek 1176
END DESCRIPTION:

--- Chimney Creek 1176.p01 (plan) ---

Plan Title=Multiple Run
Short Identifier=Multiple
Geom File=g01
Flow File=f01
Subcritical Flow
K Sum by GR= 0
Std Step Tol= 0.01
Critical Tol= 0.01
Num of Std Step Trials= 20
Max Error Tol= 0.3
Flow Tol Ratio= 0.001
Split Flow NTrial= 30
Split Flow Tol= 0.02
Split Flow Ratio= 0.02
Log Output Level= 0
Friction Slope Method= 1
Unsteady Friction Slope Method= 2
Unsteady Bridges Friction Slope Method= 1
Parabolic Critical Depth
Global Vel Dist=  1 , 1 , 1
Global Log Level= 0
CheckData=True
Encroach Param= -1, 0, 0, 0
BEGIN DESCRIPTION:
Multiple Run
END DESCRIPTION:

--- Chimney Creek 1176.f01 (steady flow) ---

Flow Title=Multiple
Number of Profiles=7
Profile Names=10-year,25-year,50-year,1pct_min,100-year,1pct_plu,500-year
River Rch & RM= Chimney Creek 11,Reach-1,13154
     215     293     356     216     431     860     639
River Rch & RM= Chimney Creek 11,Reach-1,10627
     414     587     734     456     910    1815    1417
River Rch & RM= Chimney Creek 11,Reach-1,13
     967    1403    1778    1117    2228    4445    3546
Boundary for River Rch & Prof#=Chimney Creek 11,Reach-1,1
Up Type=0
Dn Type=3
Dn Slope=0.005
Boundary for River Rch & Prof#=Chimney Creek 11,Reach-1,2
Up Type=0
Dn Type=3
Dn Slope=0.005
Boundary for River Rch & Prof#=Chimney Creek 11,Reach-1,3
Up Type=0
Dn Type=3
Dn Slope=0.005
Boundary for River Rch & Prof#=Chimney Creek 11,Reach-1,4
Up Type=0
Dn Type=3
Dn Slope=0.005
Boundary for River Rch & Prof#=Chimney Creek 11,Reach-1,5
Up Type=0
Dn Type=3
Dn Slope=0.005
Boundary for River Rch & Prof#=Chimney Creek 11,Reach-1,6
Up Type=0
Dn Type=3
Dn Slope=0.005
Boundary for River Rch & Prof#=Chimney Creek 11,Reach-1,7
Up Type=0
Dn Type=3
Dn Slope=0.005

--- Chimney Creek 1176.g01 (geometry) ---

Geom Title=Existing Conditions

River Reach=Chimney Creek 11,Reach-1
Reach XY= 30
      1651105.00      7034088.00      1650851.49      7033345.80
      1650695.18      7033327.53      1650512.83      7033094.18
      1650428.97      7032710.81      1650057.30      7032393.09
      1649915.62      7032437.40      1649818.36      7032351.35
      1649807.06      7032093.85      1649956.47      7031941.54
      1650607.45      7031732.53      1651056.55      7031341.75
      1651568.24      7031224.39      1651702.76      7031032.07
      1651758.76      7030539.56      1651952.55      7030293.46
      1652739.84      7030337.62      1652899.60      7030190.43
      1652705.52      7029572.78      1652703.80      7028848.50
      1652405.37      7027953.27      1652710.61      7027293.59
      1653299.38      7026882.38      1653574.77      7026467.87
      1654001.91      7026136.31      1653949.20      7026039.55
      1653791.76      7026074.89      1653691.64      7025774.65
      1653457.90      7025680.08      1653605.00      7025338.00

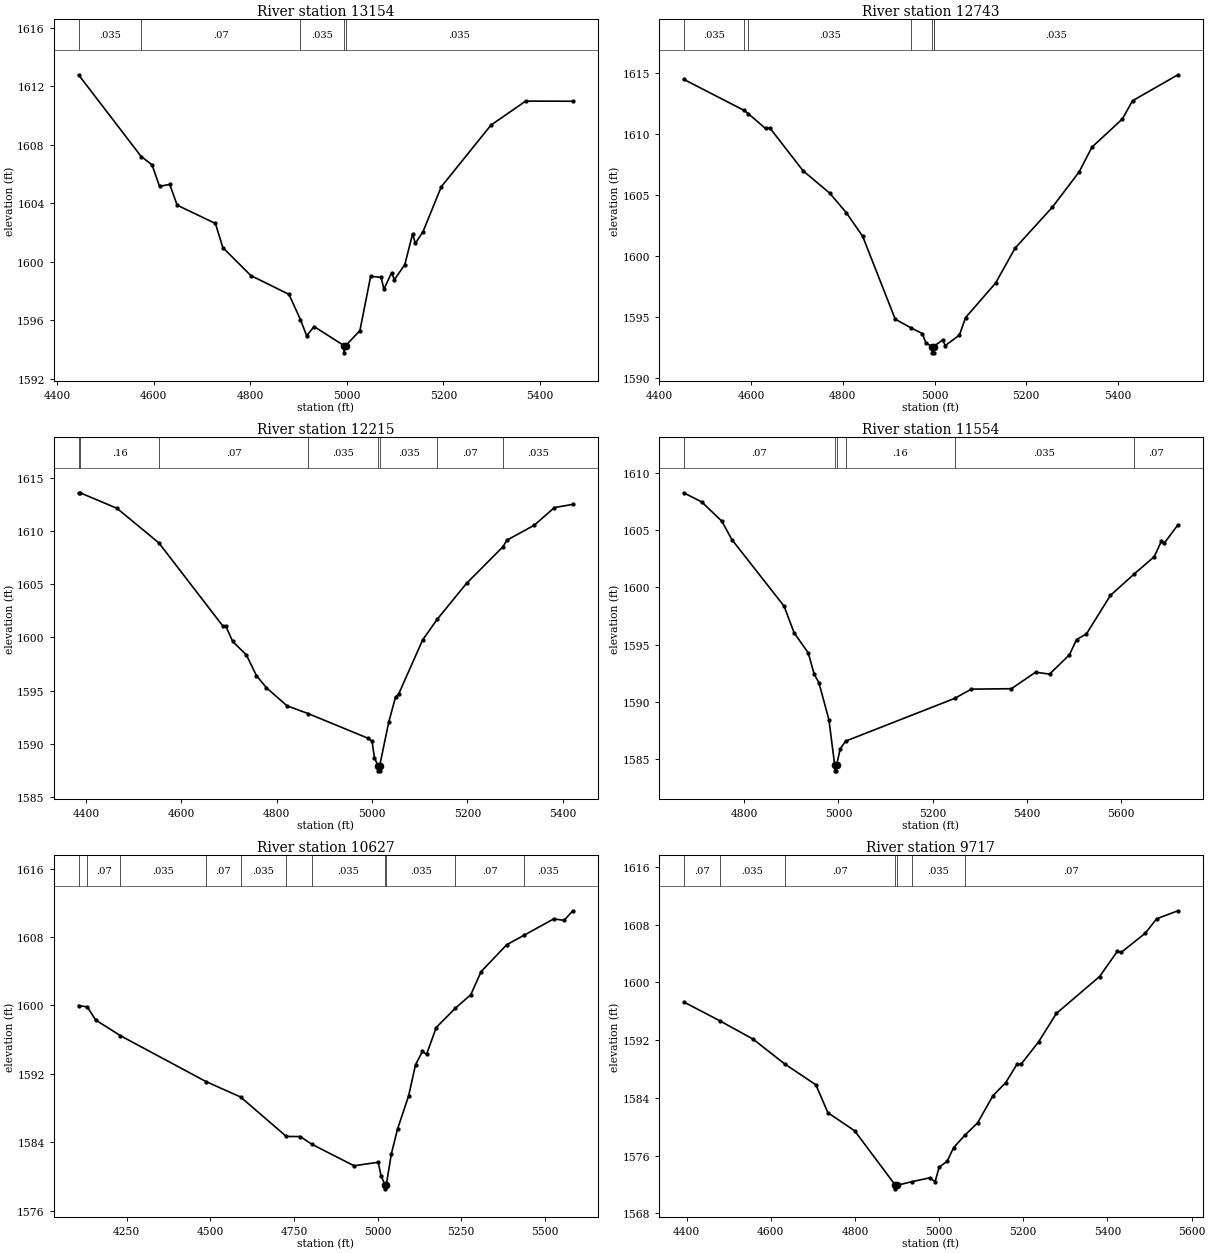
Type RM Length L Ch R = 1,13154,411,411,411
BEGIN DESCRIPTION:
Chimney Creek 1176 26.0
END DESCRIPTION:
XS GIS Cut Line= 3
      1651531.29      7033693.97      1651058.69      7033986.47
      1650649.71      7034214.60
#Sta/Elev= 30
  4444.2 1612.78  4573.9 1607.19  4596.5 1606.62  4611.9 1605.15  4633.1 1605.28
  4648.5 1603.86  4727.7 1602.61  4743.1 1600.96  4801.0 1599.05  4880.1 1597.76
  4903.8 1596.04  4916.8 1594.93  4932.1 1595.56  4993.9 1594.26  4994.2 1593.76
  4997.9 1594.26  5027.1 1595.28  5049.4 1599.00  5071.1 1598.92  5076.8 1598.11
  5092.8 1599.24  5098.5 1598.76  5120.2 1599.80  5136.2 1601.89  5142.0 1601.25
  5157.9 1602.05  5195.7 1605.12  5298.5 1609.33  5370.6 1610.98  5468.3 1610.97
#Mann=5,-1,0
  4444.2   0.035       0  4573.9    0.07       0  4903.8   0.035       0
  4993.9   0.035       0  4997.9   0.035       0
Bank Sta=4993.9,4997.9
Exp/Cntr=0.3,0.1

Type RM Length L Ch R = 1,12743,528,528,528
BEGIN DESCRIPTION:
Mapping XS 012bd9d3
END DESCRIPTION:
XS GIS Cut Line= 3
      1651465.17      7033300.38      1650999.90      7033593.78
      1650552.26      7033873.12
#Sta/Elev= 30
  4452.9 1614.49  4584.3 1611.95  4594.3 1611.66  4631.4 1610.46  4640.8 1610.51
  4713.2 1607.00  4771.5 1605.16  4807.8 1603.55  4843.2 1601.63  4914.2 1594.84
  4949.4 1594.11  4973.3 1593.66  4981.0 1592.90  4994.2 1592.58  4994.5 1592.08
  4998.0 1592.08  4998.2 1592.58  4998.6 1592.62  5017.5 1593.13  5023.4 1592.68
  5054.1 1593.53  5067.7 1594.97  5133.1 1597.80  5175.6 1600.66  5256.3 1603.99
  5315.2 1606.90  5343.1 1608.93  5409.5 1611.24  5431.6 1612.73  5530.6 1614.86
#Mann=7,-1,0
  4452.9   0.035       0  4584.3    0.07       0  4594.3   0.035       0
  4949.4    0.07       0  4994.2   0.035       0  4998.2    0.07       0
  4998.6   0.035       0
Bank Sta=4994.2,4998.2
Exp/Cntr=0.3,0.1

Type RM Length L Ch R = 1,12215,661,661,661
BEGIN DESCRIPTION:
Mapping XS c513b30d
END DESCRIPTION:
XS GIS Cut Line= 3
      1651134.86      7032904.56      1650642.26      7033284.32
      1650327.63      7033555.55
#Sta/Elev= 30
  4384.0 1613.60  4387.2 1613.60  4464.6 1612.14  4552.5 1608.89  4686.6 1601.09
  4692.9 1601.07  4707.4 1599.63  4736.4 1598.34  4757.2 1596.42  4778.1 1595.28
  4821.6 1593.57  4866.5 1592.83  4991.8 1590.52  5000.0 1590.23  5004.9 1588.71
  5012.1 1587.96  5012.4 1587.46  5015.9 1587.46  5016.1 1587.96  5035.0 1592.04
  5049.3 1594.40  5055.9 1594.69  5106.3 1599.78  5137.1 1601.73  5198.4 1605.09
  5274.6 1608.52  5282.9 1609.14  5340.0 1610.54  5382.8 1612.21  5421.4 1612.51
#Mann=8,-1,0
  4384.0   0.035       0  4387.2    0.16       0  4552.5    0.07       0
  4866.5   0.035       0  5012.1   0.035       0  5016.1   0.035       0
  5137.1    0.07       0  5274.6   0.035       0
Bank Sta=5012.1,5016.1
Exp/Cntr=0.3,0.1

Type RM Length L Ch R = 1,11554,927,927,927
BEGIN DESCRIPTION:
Mapping XS a778b62d
END DESCRIPTION:
XS GIS Cut Line= 3
      1650711.88      7032542.62      1650425.46      7032714.47
      1649830.00      7033112.03
#Sta/Elev= 30
  4671.2 1608.29  4709.6 1607.49  4752.4 1605.80  4773.7 1604.19  4884.5 1598.37
  4905.9 1596.03  4935.8 1594.28  4948.7 1592.39  4958.4 1591.68  4979.8 1588.43
  4992.1 1584.45  4992.3 1583.95  4995.8 1583.95  4996.1 1584.45  5003.8 1585.87
  5015.2 1586.55  5246.8 1590.29  5282.3 1591.10  5367.6 1591.14  5418.7 1592.58
  5448.7 1592.42  5490.8 1594.11  5505.8 1595.44  5526.8 1595.93  5577.9 1599.31
  5628.6 1601.19  5671.0 1602.70  5686.0 1604.05  5692.0 1603.87  5721.2 1605.48
#Mann=6,-1,0
  4671.2    0.07       0  4992.1    0.07       0  4996.1    0.07       0
  5015.2    0.16       0  5246.8   0.035       0  5628.6    0.07       0
Bank Sta=4992.1,4996.1
Exp/Cntr=0.3,0.1

Type RM Length L Ch R = 1,10627,910,910,910
BEGIN DESCRIPTION:
Mapping XS 51e9430d
END DESCRIPTION:
XS GIS Cut Line= 3
      1650695.58      7032286.61      1649805.79      7032217.16
      1649239.65      7032362.50
#Sta/Elev= 30
  4106.6 1599.99  4132.6 1599.83  4157.7 1598.30  4231.8 1596.46  4487.5 1591.09
  4590.7 1589.29  4727.5 1584.67  4769.2 1584.66  4803.0 1583.77  4929.7 1581.24
  5002.1 1581.65  5010.2 1580.10  5022.0 1579.04  5022.3 1578.54  5026.3 1579.04
  5041.2 1582.62  5059.7 1585.53  5092.8 1589.41  5113.5 1593.06  5134.1 1594.62
  5146.4 1594.27  5175.4 1597.42  5232.0 1599.66  5278.7 1601.26  5309.6 1603.97
  5385.8 1607.10  5438.0 1608.22  5526.5 1610.13  5557.4 1609.96  5583.6 1611.08
#Mann=11,-1,0
  4106.6   0.035       0  4132.6    0.07       0  4231.8   0.035       0
  4487.5    0.07       0  4590.7   0.035       0  4727.5    0.16       0
  4803.0   0.035       0  5022.0   0.035       0  5026.3   0.035       0
  5232.0    0.07       0  5438.0   0.035       0
Bank Sta=5022,5026.3
Exp/Cntr=0.3,0.1

Type RM Length L Ch R = 1,9717,953,953,953
BEGIN DESCRIPTION:
Mapping XS f81dd418
END DESCRIPTION:
XS GIS Cut Line= 3
      1650853.84      7032202.14      1650458.86      7031739.88
      1650149.26      7031265.74
#Sta/Elev= 30
  4393.1 1597.28  4478.6 1594.68  4558.0 1592.13  4633.5 1588.68  4707.3 1585.80
  4735.8 1581.94  4799.5 1579.43  4896.1 1571.90  4896.4 1571.40  4900.6 1571.90
  4936.2 1572.40  4977.3 1572.92  4990.5 1572.40  5000.2 1574.40  5019.3 1575.23
  5034.4 1577.09  5060.6 1578.79  5091.7 1580.55  5127.9 1584.29  5158.2 1586.10
  5185.2 1588.67  5194.4 1588.63  5236.5 1591.76  5278.7 1595.69  5381.4 1600.80
  5423.5 1604.29  5432.7 1604.14  5490.0 1606.80  5517.0 1608.80  5567.4 1609.90
#Mann=7,-1,0
  4393.1    0.07       0  4478.6   0.035       0  4633.5    0.07       0
  4896.1   0.035       0  4900.6    0.07       0  4936.2   0.035       0
  5060.6    0.07       0
Bank Sta=4896.1,4900.6
Exp/Cntr=0.3,0.1

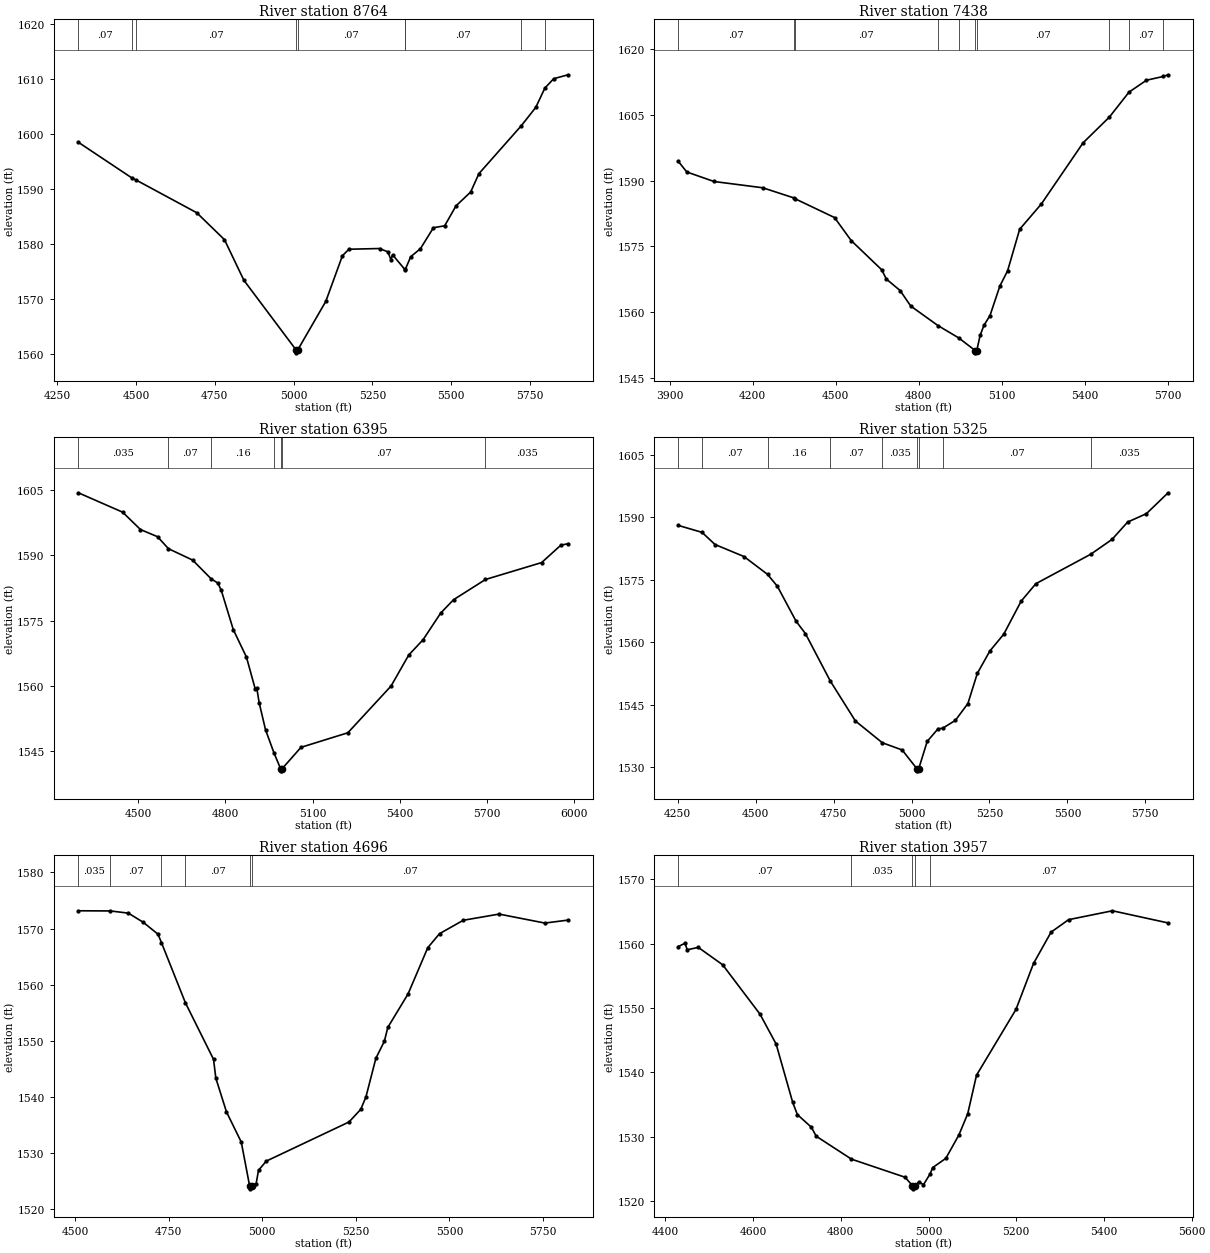
Type RM Length L Ch R = 1,8764,1326,1326,1326
BEGIN DESCRIPTION:
Mapping XS 817a9847
END DESCRIPTION:
XS GIS Cut Line= 3
      1651537.40      7031959.89      1651256.16      7031340.14
      1651045.23      7030493.81
#Sta/Elev= 30
  4317.3 1598.46  4487.6 1591.97  4500.2 1591.62  4692.7 1585.68  4780.6 1580.80
  4842.2 1573.43  5008.1 1560.77  5008.4 1560.27  5012.7 1560.77  5102.0 1569.61
  5154.7 1577.89  5175.3 1579.06  5272.3 1579.19  5299.0 1578.58  5308.5 1577.14
  5313.6 1578.06  5353.1 1575.36  5354.1 1575.40  5371.1 1577.70  5402.0 1579.16
  5443.2 1582.96  5478.8 1583.31  5514.9 1586.93  5561.3 1589.44  5587.5 1592.77
  5722.0 1601.47  5767.8 1604.79  5796.5 1608.28  5824.6 1609.99  5870.1 1610.70
#Mann=9,-1,0
  4317.3    0.07       0  4487.6   0.035       0  4500.2    0.07       0
  5008.1    0.07       0  5012.7    0.07       0  5353.1    0.16       0
  5354.1    0.07       0  5722.0    0.16       0  5796.5    0.07       0
Bank Sta=5008.1,5012.7
Exp/Cntr=0.3,0.1

Type RM Length L Ch R = 1,7438,1043,1043,1043
BEGIN DESCRIPTION:
Mapping XS 27392c9d
END DESCRIPTION:
XS GIS Cut Line= 3
      1652380.80      7031304.87      1651886.03      7030358.72
      1651482.89      7029782.19
#Sta/Elev= 30
  3930.9 1594.36  3961.2 1591.97  4059.6 1589.80  4236.2 1588.37  4348.5 1586.06
  4351.2 1585.92  4495.5 1581.59  4556.1 1576.33  4666.4 1569.68  4682.9 1567.58
  4732.7 1564.97  4771.2 1561.43  4869.9 1556.97  4945.1 1554.16  5004.7 1551.27
  5005.2 1550.77  5010.0 1551.27  5022.2 1554.76  5036.1 1557.04  5057.9 1559.27
  5093.7 1566.01  5121.5 1569.45  5165.2 1578.92  5243.5 1584.67  5394.6 1598.61
  5489.6 1604.47  5560.7 1610.16  5623.9 1612.87  5685.4 1613.74  5702.1 1614.11
#Mann=10,-1,0
  3930.9    0.07       0  4348.5   0.035       0  4351.2    0.07       0
  4869.9   0.035       0  4945.1    0.07       0  5004.7    0.07       0
  5010.0    0.07       0  5489.6   0.035       0  5560.7    0.07       0
  5685.4   0.035       0
Bank Sta=5004.7,5010
Exp/Cntr=0.3,0.1

Type RM Length L Ch R = 1,6395,1070,1070,1070
BEGIN DESCRIPTION:
Mapping XS bdb695ec
END DESCRIPTION:
XS GIS Cut Line= 3
      1653494.52      7030529.72      1652848.70      7030245.00
      1651980.65      7029790.14
#Sta/Elev= 30
  4293.9 1604.30  4446.4 1599.85  4507.7 1595.87  4566.6 1594.22  4604.0 1591.48
  4687.3 1588.86  4750.8 1584.58  4774.2 1583.58  4786.1 1581.89  4827.3 1572.91
  4872.6 1566.61  4902.7 1559.33  4908.2 1559.48  4916.3 1556.16  4938.2 1549.96
  4967.4 1544.62  4990.1 1541.02  4990.5 1540.52  4995.6 1541.02  5060.3 1545.91
  5221.7 1549.25  5370.5 1559.98  5431.1 1567.07  5480.8 1570.61  5541.4 1576.72
  5585.5 1579.77  5695.4 1584.41  5888.7 1588.29  5954.9 1592.28  5979.7 1592.62
#Mann=7,-1,0
  4293.9   0.035       0  4604.0    0.07       0  4750.8    0.16       0
  4967.4    0.07       0  4990.1    0.07       0  4995.6    0.07       0
  5695.4   0.035       0
Bank Sta=4990.1,4995.6
Exp/Cntr=0.3,0.1

Type RM Length L Ch R = 1,5325,629,629,629
BEGIN DESCRIPTION:
Mapping XS 4a8559bc
END DESCRIPTION:
XS GIS Cut Line= 3
      1653452.28      7029234.55      1652705.76      7029264.93
      1651885.71      7029343.03
#Sta/Elev= 30
  4252.1 1587.98  4328.0 1586.32  4369.5 1583.41  4462.3 1580.53  4538.0 1576.25
  4569.6 1573.39  4629.7 1564.99  4659.7 1562.02  4739.4 1550.65  4819.8 1541.08
  4906.2 1535.85  4970.0 1534.11  5017.2 1529.61  5017.7 1529.11  5023.0 1529.61
  5050.2 1536.17  5084.9 1539.19  5099.9 1539.33  5140.6 1541.22  5180.8 1545.26
  5210.9 1552.48  5251.1 1557.85  5295.8 1561.90  5351.6 1569.82  5398.8 1574.01
  5574.7 1581.07  5642.9 1584.62  5693.1 1588.79  5753.4 1590.81  5823.0 1595.82
#Mann=9,-1,0
  4252.1   0.035       0  4328.0    0.07       0  4538.0    0.16       0
  4739.4    0.07       0  4906.2   0.035       0  5017.2   0.035       0
  5023.0   0.035       0  5099.9    0.07       0  5574.7   0.035       0
Bank Sta=5017.2,5023
Exp/Cntr=0.3,0.1

Type RM Length L Ch R = 1,4696,739,739,739
BEGIN DESCRIPTION:
Mapping XS 60fb0bd3
END DESCRIPTION:
XS GIS Cut Line= 3
      1653079.35      7028537.78      1652604.05      7028668.00
      1651828.53      7028921.45
#Sta/Elev= 30
  4508.4 1573.16  4594.1 1573.13  4642.1 1572.74  4681.8 1571.11  4721.4 1568.98
  4730.6 1567.47  4794.5 1556.77  4869.7 1546.69  4875.8 1543.35  4904.2 1537.34
  4943.8 1531.95  4966.2 1524.12  4966.7 1523.62  4972.0 1524.12  4983.5 1524.53
  4989.9 1526.93  5010.7 1528.56  5231.7 1535.53  5263.2 1537.79  5276.9 1539.98
  5303.5 1546.87  5326.3 1549.93  5335.4 1552.38  5389.5 1558.34  5442.1 1566.57
  5473.6 1569.08  5537.2 1571.47  5632.8 1572.57  5755.1 1570.97  5817.1 1571.50
#Mann=6,-1,0
  4508.4   0.035       0  4594.1    0.07       0  4730.6    0.16       0
  4794.5    0.07       0  4966.2    0.07       0  4972.0    0.07       0
Bank Sta=4966.2,4972
Exp/Cntr=0.3,0.1

Type RM Length L Ch R = 1,3957,459,459,459
BEGIN DESCRIPTION:
Mapping XS c57c222e
END DESCRIPTION:
XS GIS Cut Line= 3
      1652939.56      7028189.76      1652401.39      7027991.85
      1651858.10      7027991.85
#Sta/Elev= 30
  4429.6 1559.54  4444.5 1560.04  4449.8 1559.04  4475.0 1559.40  4530.4 1556.71
  4615.6 1549.04  4652.4 1544.40  4690.2 1535.34  4700.8 1533.44  4732.8 1531.47
  4743.9 1530.07  4824.3 1526.51  4946.5 1523.70  4963.3 1522.40  4963.8 1521.90
  4969.2 1522.40  4977.9 1522.97  4988.5 1522.55  5003.5 1524.21  5009.4 1525.20
  5039.4 1526.63  5069.4 1530.29  5089.4 1533.58  5109.4 1539.55  5199.4 1549.77
  5239.4 1556.91  5279.4 1561.77  5319.4 1563.71  5419.4 1565.09  5546.3 1563.20
#Mann=5,-1,0
  4429.6    0.07       0  4824.3   0.035       0  4963.3   0.035       0
  4969.2   0.035       0  5003.5    0.07       0
Bank Sta=4963.3,4969.2
Exp/Cntr=0.3,0.1

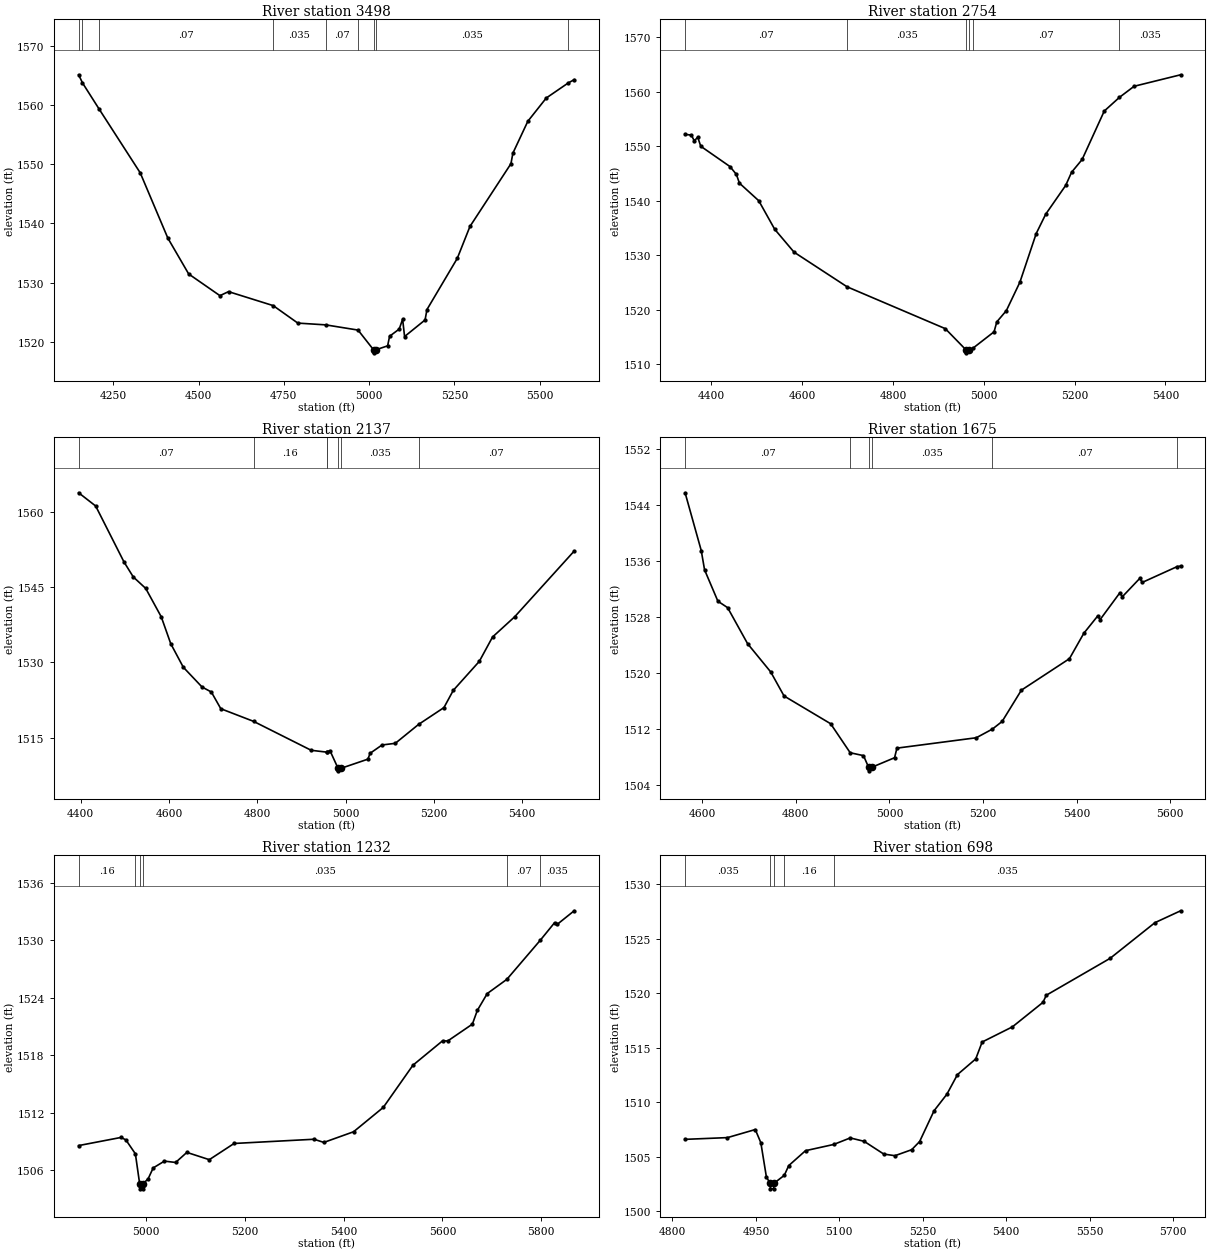
Type RM Length L Ch R = 1,3498,744,744,744
BEGIN DESCRIPTION:
Mapping XS 2452a982
END DESCRIPTION:
XS GIS Cut Line= 3
      1653352.80      7027873.80      1652554.17      7027582.13
      1652022.89      7027297.39
#Sta/Elev= 30
  4148.2 1565.06  4159.5 1563.69  4208.1 1559.29  4328.8 1548.51  4409.8 1537.49
  4470.9 1531.44  4562.5 1527.78  4587.7 1528.46  4718.7 1526.10  4790.9 1523.15
  4872.8 1522.85  4967.5 1521.97  5013.1 1518.63  5013.6 1518.13  5019.1 1518.63
  5054.2 1519.31  5060.0 1520.93  5088.2 1522.14  5098.2 1523.81  5103.9 1520.88
  5164.0 1523.68  5169.6 1525.44  5258.4 1534.07  5295.6 1539.46  5415.8 1550.05
  5421.5 1551.83  5465.3 1557.21  5519.4 1561.14  5584.3 1563.70  5601.2 1564.23
#Mann=9,-1,0
  4148.2    0.07       0  4159.5    0.16       0  4208.1    0.07       0
  4718.7   0.035       0  4872.8    0.07       0  4967.5   0.035       0
  5013.1   0.035       0  5019.1   0.035       0  5584.3   0.035       0
Bank Sta=5013.1,5019.1
Exp/Cntr=0.3,0.1

Type RM Length L Ch R = 1,2754,617,617,617
BEGIN DESCRIPTION:
Mapping XS fa61a8ff
END DESCRIPTION:
XS GIS Cut Line= 3
      1653509.41      7027512.71      1653023.27      7027068.24
      1652665.64      7026825.20
#Sta/Elev= 30
  4342.3 1552.17  4355.9 1552.06  4362.6 1550.99  4370.1 1551.66  4376.8 1550.00
  4441.0 1546.28  4455.2 1544.84  4461.9 1543.23  4504.5 1540.00  4539.6 1534.76
  4582.2 1530.56  4699.0 1524.20  4915.2 1516.52  4961.3 1512.58  4961.8 1512.08
  4967.7 1512.58  4977.0 1512.99  5022.6 1515.94  5028.6 1517.76  5049.6 1519.82
  5079.5 1525.05  5115.4 1533.98  5136.4 1537.54  5180.3 1542.81  5193.3 1545.23
  5216.5 1547.57  5265.2 1556.46  5298.7 1558.98  5331.0 1561.01  5433.4 1563.12
#Mann=6,-1,0
  4342.3    0.07       0  4699.0   0.035       0  4961.3    0.07       0
  4967.7   0.035       0  4977.0    0.07       0  5298.7   0.035       0
Bank Sta=4961.3,4967.7
Exp/Cntr=0.3,0.1

Type RM Length L Ch R = 1,2137,462,462,462
BEGIN DESCRIPTION:
Mapping XS 7f673ea7
END DESCRIPTION:
XS GIS Cut Line= 3
      1653912.19      7027085.64      1653467.71      7026675.88
      1652950.39      7026648.11
#Sta/Elev= 30
  4395.3 1563.83  4433.9 1561.19  4498.0 1550.04  4519.0 1547.05  4547.3 1544.75
  4582.5 1539.08  4604.0 1533.72  4632.4 1529.03  4674.9 1525.08  4695.9 1524.09
  4717.4 1520.75  4791.6 1518.23  4922.1 1512.46  4957.4 1512.09  4958.9 1512.14
  4964.7 1512.39  4983.0 1508.86  4983.5 1508.36  4989.5 1508.86  5050.6 1510.69
  5055.6 1511.86  5082.7 1513.52  5112.7 1513.85  5165.4 1517.62  5222.9 1520.98
  5244.0 1524.41  5303.0 1530.20  5333.0 1535.06  5383.1 1539.09  5517.9 1552.20
#Mann=7,-1,0
  4395.3    0.07       0  4791.6    0.16       0  4957.4    0.07       0
  4958.9   0.035       0  4983.0   0.035       0  4989.5   0.035       0
  5165.4    0.07       0
Bank Sta=4983,4989.5
Exp/Cntr=0.3,0.1

Type RM Length L Ch R = 1,1675,443,443,443
BEGIN DESCRIPTION:
Mapping XS 2dba139c
END DESCRIPTION:
XS GIS Cut Line= 3
      1654037.76      7026673.90      1653749.54      7026345.74
      1653143.60      7026203.37
#Sta/Elev= 30
  4563.3 1545.76  4597.8 1537.52  4604.9 1534.77  4633.4 1530.29  4654.2 1529.37
  4696.9 1524.23  4746.3 1520.20  4774.8 1516.77  4874.4 1512.81  4916.2 1508.67
  4944.6 1508.26  4955.6 1506.59  4956.1 1506.09  4962.1 1506.59  5011.0 1507.96
  5016.1 1509.33  5185.7 1510.81  5220.2 1512.05  5241.0 1513.14  5282.1 1517.60
  5384.8 1522.09  5415.6 1525.72  5445.3 1528.19  5450.4 1527.67  5492.8 1531.51
  5497.9 1530.93  5535.2 1533.55  5540.4 1532.97  5615.1 1535.23  5622.5 1535.30
#Mann=6,-1,0
  4563.3    0.07       0  4916.2   0.035       0  4955.6   0.035       0
  4962.1   0.035       0  5220.2    0.07       0  5615.1   0.035       0
Bank Sta=4955.6,4962.1
Exp/Cntr=0.3,0.1

Type RM Length L Ch R = 1,1232,534,534,534
BEGIN DESCRIPTION:
Mapping XS 28031bbf
END DESCRIPTION:
XS GIS Cut Line= 4
      1654022.12      7025935.99      1653983.91      7026071.44
      1653789.47      7026175.60      1653149.43      7026140.91
#Sta/Elev= 30
  4864.1 1508.59  4950.0 1509.44  4959.7 1509.18  4978.9 1507.73  4987.6 1504.58
  4988.1 1504.08  4993.6 1504.08  4994.1 1504.58  5004.8 1505.14  5014.9 1506.26
  5037.6 1506.97  5060.3 1506.83  5083.0 1507.88  5128.4 1507.12  5178.5 1508.81
  5340.1 1509.25  5360.1 1508.92  5420.2 1510.03  5480.3 1512.57  5540.3 1516.97
  5600.4 1519.52  5610.5 1519.49  5660.5 1521.25  5670.5 1522.68  5690.6 1524.44
  5730.2 1525.92  5797.9 1530.00  5826.8 1531.83  5831.8 1531.64  5866.4 1533.07
#Mann=6,-1,0
  4864.1    0.16       0  4978.9   0.035       0  4987.6   0.035       0
  4994.1   0.035       0  5730.2    0.07       0  5797.9   0.035       0
Bank Sta=4987.6,4994.1
Exp/Cntr=0.3,0.1

Type RM Length L Ch R = 1,698,685,685,685
BEGIN DESCRIPTION:
Mapping XS 38e1e3c7
END DESCRIPTION:
XS GIS Cut Line= 4
      1653881.09      7025806.07      1653703.95      7025798.43
      1653414.56      7025827.77      1653029.71      7026002.90
#Sta/Elev= 30
  4822.7 1506.59  4898.9 1506.75  4948.9 1507.49  4958.9 1506.28  4968.9 1503.13
  4975.7 1502.55  4976.2 1502.05  4981.7 1502.05  4982.2 1502.55  5001.1 1503.29
  5009.0 1504.18  5039.2 1505.55  5089.8 1506.12  5119.6 1506.72  5144.6 1506.41
  5179.9 1505.24  5200.0 1505.09  5230.1 1505.64  5244.4 1506.39  5270.3 1509.21
  5293.4 1510.73  5312.4 1512.53  5345.3 1513.97  5356.8 1515.52  5411.2 1516.91
  5466.2 1519.16  5472.1 1519.81  5587.0 1523.20  5667.5 1526.47  5713.7 1527.56
#Mann=5,-1,0
  4822.7   0.035       0  4975.7   0.035       0  4982.2   0.035       0
  5001.1    0.16       0  5089.8   0.035       0
Bank Sta=4975.7,4982.2
Exp/Cntr=0.3,0.1

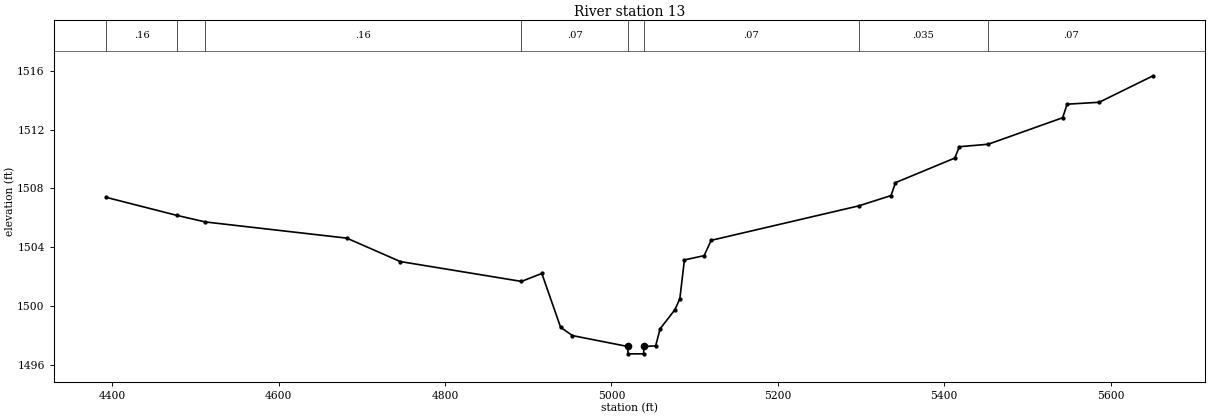
Type RM Length L Ch R = 1,13,0,0,0
BEGIN DESCRIPTION:
Chimney Creek 1176 1.0
END DESCRIPTION:
XS GIS Cut Line= 3
      1653978.55      7025830.13      1653605.43      7025350.98
      1653005.30      7025603.26
#Sta/Elev= 30
  4392.7 1507.39  4478.1 1506.16  4511.8 1505.72  4681.9 1504.62  4746.2 1503.03
  4891.8 1501.68  4916.3 1502.22  4938.9 1498.56  4953.1 1498.00  5019.5 1497.26
  5020.0 1496.76  5038.6 1496.76  5039.1 1497.26  5053.1 1497.30  5058.5 1498.46
  5076.4 1499.77  5082.2 1500.51  5087.7 1503.14  5111.4 1503.43  5119.8 1504.47
  5297.1 1506.81  5336.0 1507.51  5341.4 1508.39  5412.7 1510.06  5418.1 1510.83
  5452.9 1511.00  5542.3 1512.80  5547.7 1513.72  5586.2 1513.85  5651.0 1515.65
#Mann=8,-1,0
  4392.7    0.16       0  4478.1   0.035       0  4511.8    0.16       0
  4891.8    0.07       0  5019.5    0.07       0  5039.1    0.07       0
  5297.1   0.035       0  5452.9    0.07       0
Bank Sta=5019.5,5039.1
Exp/Cntr=0.3,0.1

Chan Stop Cuts=-1