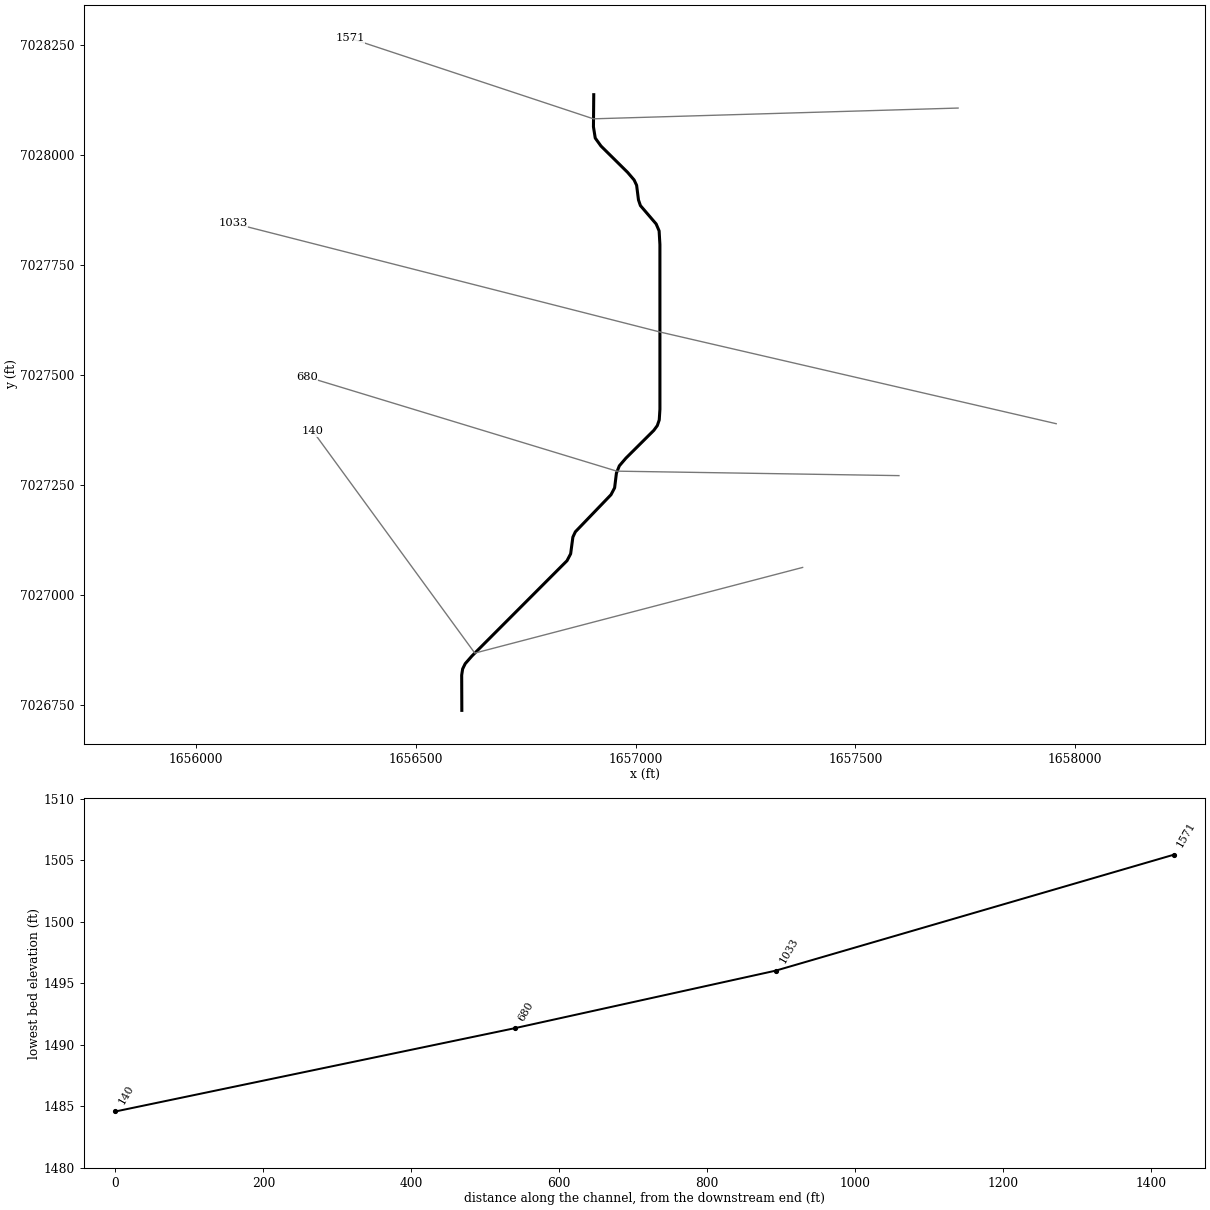
--- Chimney Creek 1177.prj (project) ---

Proj Title=Chimney Creek 1177 Base Level Engineering
Current Plan=p01
Default Exp/Contr=0.3,0.1
English Units
Geom File=g01
Flow File=f01
Plan File=p01
BEGIN DESCRIPTION:
Chimney Creek 1177
END DESCRIPTION:

--- Chimney Creek 1177.p01 (plan) ---

Plan Title=Multiple Run
Short Identifier=Multiple
Geom File=g01
Flow File=f01
Subcritical Flow
K Sum by GR= 0
Std Step Tol= 0.01
Critical Tol= 0.01
Num of Std Step Trials= 20
Max Error Tol= 0.3
Flow Tol Ratio= 0.001
Split Flow NTrial= 30
Split Flow Tol= 0.02
Split Flow Ratio= 0.02
Log Output Level= 0
Friction Slope Method= 1
Unsteady Friction Slope Method= 2
Unsteady Bridges Friction Slope Method= 1
Parabolic Critical Depth
Global Vel Dist=  1 , 1 , 1
Global Log Level= 0
CheckData=True
Encroach Param= -1, 0, 0, 0
BEGIN DESCRIPTION:
Multiple Run
END DESCRIPTION:

--- Chimney Creek 1177.f01 (steady flow) ---

Flow Title=Multiple
Number of Profiles=7
Profile Names=10-year,25-year,50-year,1pct_min,100-year,1pct_plu,500-year
River Rch & RM= Chimney Creek 11,Reach-1,1571
     301     426     533     332     663    1323    1040
River Rch & RM= Chimney Creek 11,Reach-1,1033
     359     514     647     406     810    1617    1287
Boundary for River Rch & Prof#=Chimney Creek 11,Reach-1,1
Up Type=0
Dn Type=3
Dn Slope=0.005
Boundary for River Rch & Prof#=Chimney Creek 11,Reach-1,2
Up Type=0
Dn Type=3
Dn Slope=0.005
Boundary for River Rch & Prof#=Chimney Creek 11,Reach-1,3
Up Type=0
Dn Type=3
Dn Slope=0.005
Boundary for River Rch & Prof#=Chimney Creek 11,Reach-1,4
Up Type=0
Dn Type=3
Dn Slope=0.005
Boundary for River Rch & Prof#=Chimney Creek 11,Reach-1,5
Up Type=0
Dn Type=3
Dn Slope=0.005
Boundary for River Rch & Prof#=Chimney Creek 11,Reach-1,6
Up Type=0
Dn Type=3
Dn Slope=0.005
Boundary for River Rch & Prof#=Chimney Creek 11,Reach-1,7
Up Type=0
Dn Type=3
Dn Slope=0.005

--- Chimney Creek 1177.g01 (geometry) ---

Geom Title=Existing Conditions

River Reach=Chimney Creek 11,Reach-1
Reach XY= 30
      1656905.00      7028138.00      1656904.33      7028065.00
      1656908.39      7028039.41      1656921.46      7028021.25
      1656981.94      7027961.45      1656996.84      7027944.05
      1657002.50      7027931.96      1657006.72      7027898.71
      1657011.14      7027885.83      1657046.91      7027844.08
      1657053.64      7027828.35      1657055.46      7027797.28
      1657055.49      7027422.80      1657053.95      7027398.44
      1657049.53      7027385.55      1657041.60      7027374.69
      1656978.07      7027311.44      1656963.18      7027294.04
      1656956.55      7027277.36      1656952.46      7027244.05
      1656944.20      7027228.33      1656863.18      7027144.04
      1656857.54      7027131.95      1656852.47      7027094.05
      1656844.22      7027078.32      1656627.88      7026861.52
      1656612.74      7026844.22      1656606.86      7026832.23
      1656604.67      7026818.14      1656605.00      7026738.00

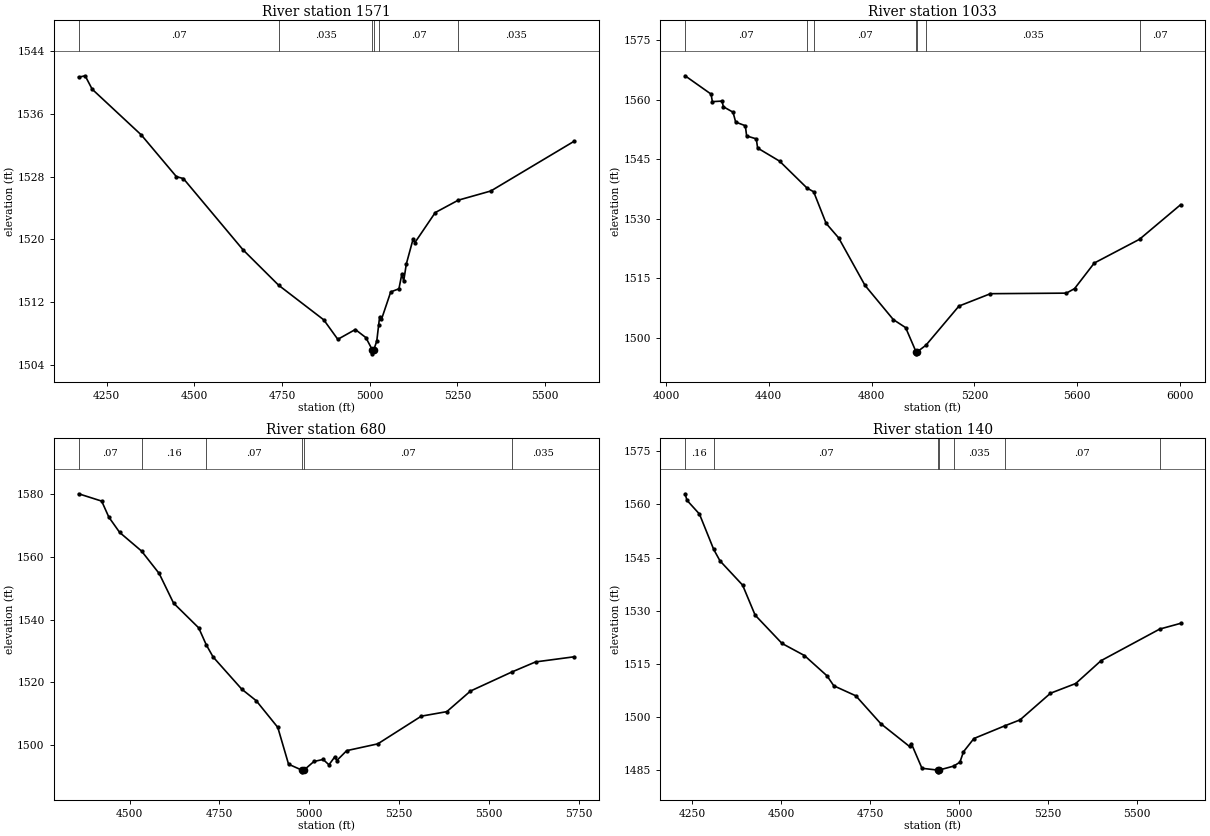
Type RM Length L Ch R = 1,1571,538,538,538
BEGIN DESCRIPTION:
Chimney Creek 1177 3.0
END DESCRIPTION:
XS GIS Cut Line= 3
      1657733.59      7028107.64      1656904.25      7028083.14
      1656350.73      7028266.50
#Sta/Elev= 30
  4170.3 1540.68  4188.9 1540.86  4208.9 1539.15  4349.0 1533.32  4449.0 1528.01
  4469.0 1527.76  4639.1 1518.68  4740.6 1514.17  4869.2 1509.76  4909.2 1507.28
  4959.2 1508.53  4989.2 1507.50  5007.7 1505.93  5008.0 1505.43  5011.7 1505.93
  5020.3 1507.06  5025.7 1509.11  5028.4 1510.14  5033.7 1509.82  5060.1 1513.32
  5083.5 1513.72  5091.8 1515.60  5097.1 1514.72  5104.6 1516.89  5123.6 1520.01
  5128.8 1519.59  5187.0 1523.43  5252.7 1525.01  5345.5 1526.18  5583.1 1532.52
#Mann=6,-1,0
  4170.3    0.07       0  4740.6   0.035       0  5007.7   0.035       0
  5011.7   0.035       0  5025.7    0.07       0  5252.7   0.035       0
Bank Sta=5007.7,5011.7
Exp/Cntr=0.3,0.1

Type RM Length L Ch R = 1,1033,353,353,353
BEGIN DESCRIPTION:
Mapping XS c90d0da0
END DESCRIPTION:
XS GIS Cut Line= 3
      1657956.68      7027389.85      1657055.01      7027598.52
      1656084.34      7027845.91
#Sta/Elev= 30
  4074.5 1566.05  4175.5 1561.43  4180.6 1559.53  4218.2 1559.68  4223.3 1558.25
  4260.9 1556.88  4271.2 1554.38  4308.7 1553.47  4313.8 1550.90  4351.4 1550.16
  4356.5 1547.85  4441.9 1544.55  4548.7 1537.77  4574.5 1536.83  4623.0 1528.87
  4671.6 1525.22  4774.2 1513.25  4884.4 1504.63  4932.2 1502.61  4972.8 1496.51
  4973.1 1496.01  4977.0 1496.51  5011.0 1498.17  5139.5 1508.04  5262.1 1511.16
  5557.3 1511.30  5589.2 1512.44  5665.8 1518.88  5841.8 1524.87  6001.7 1533.58
#Mann=7,-1,0
  4074.5    0.07       0  4548.7    0.16       0  4574.5    0.07       0
  4972.8    0.07       0  4977.0    0.07       0  5011.0   0.035       0
  5841.8    0.07       0
Bank Sta=4972.8,4977
Exp/Cntr=0.3,0.1

Type RM Length L Ch R = 1,680,540,540,540
BEGIN DESCRIPTION:
Mapping XS 82e938f5
END DESCRIPTION:
XS GIS Cut Line= 3
      1657599.06      7027271.79      1656957.54      7027281.95
      1656252.27      7027496.53
#Sta/Elev= 30
  4358.4 1580.17  4422.5 1577.83  4442.5 1572.70  4472.5 1567.83  4533.4 1561.88
  4582.5 1554.70  4622.5 1545.24  4692.5 1537.33  4713.6 1531.89  4732.5 1528.04
  4812.5 1517.72  4852.5 1514.06  4912.5 1505.54  4942.5 1493.77  4980.4 1491.83
  4980.7 1491.33  4984.7 1491.83  5013.1 1494.64  5038.6 1495.29  5054.9 1493.58
  5071.5 1496.17  5076.7 1494.94  5104.3 1498.10  5190.8 1500.27  5311.9 1509.12
  5382.8 1510.56  5448.6 1517.14  5563.0 1523.19  5629.8 1526.45  5737.2 1528.09
#Mann=6,-1,0
  4358.4    0.07       0  4533.4    0.16       0  4713.6    0.07       0
  4980.4    0.07       0  4984.7    0.07       0  5563.0   0.035       0
Bank Sta=4980.4,4984.7
Exp/Cntr=0.3,0.1

Type RM Length L Ch R = 1,140,0,0,0
BEGIN DESCRIPTION:
Chimney Creek 1177 1.0
END DESCRIPTION:
XS GIS Cut Line= 3
      1657380.00      7027063.00      1656634.53      7026868.19
      1656266.62      7027372.44
#Sta/Elev= 30
  4229.5 1562.98  4234.7 1561.15  4269.9 1557.26  4310.0 1547.29  4327.7 1544.06
  4391.3 1537.23  4426.6 1528.76  4502.3 1520.77  4565.4 1517.36  4628.8 1511.65
  4648.1 1508.82  4710.1 1506.00  4780.3 1498.14  4861.2 1491.71  4866.3 1492.52
  4896.2 1485.56  4939.9 1485.06  4940.2 1484.56  4944.2 1485.06  4985.5 1486.18
  5003.0 1487.29  5013.0 1490.22  5042.4 1493.96  5129.6 1497.55  5172.1 1499.21
  5257.9 1506.73  5328.9 1509.47  5400.0 1515.90  5565.2 1524.82  5624.2 1526.44
#Mann=7,-1,0
  4229.5    0.16       0  4310.0    0.07       0  4939.9   0.035       0
  4944.2    0.07       0  4985.5   0.035       0  5129.6    0.07       0
  5565.2   0.035       0
Bank Sta=4939.9,4944.2
Exp/Cntr=0.3,0.1

Chan Stop Cuts=-1