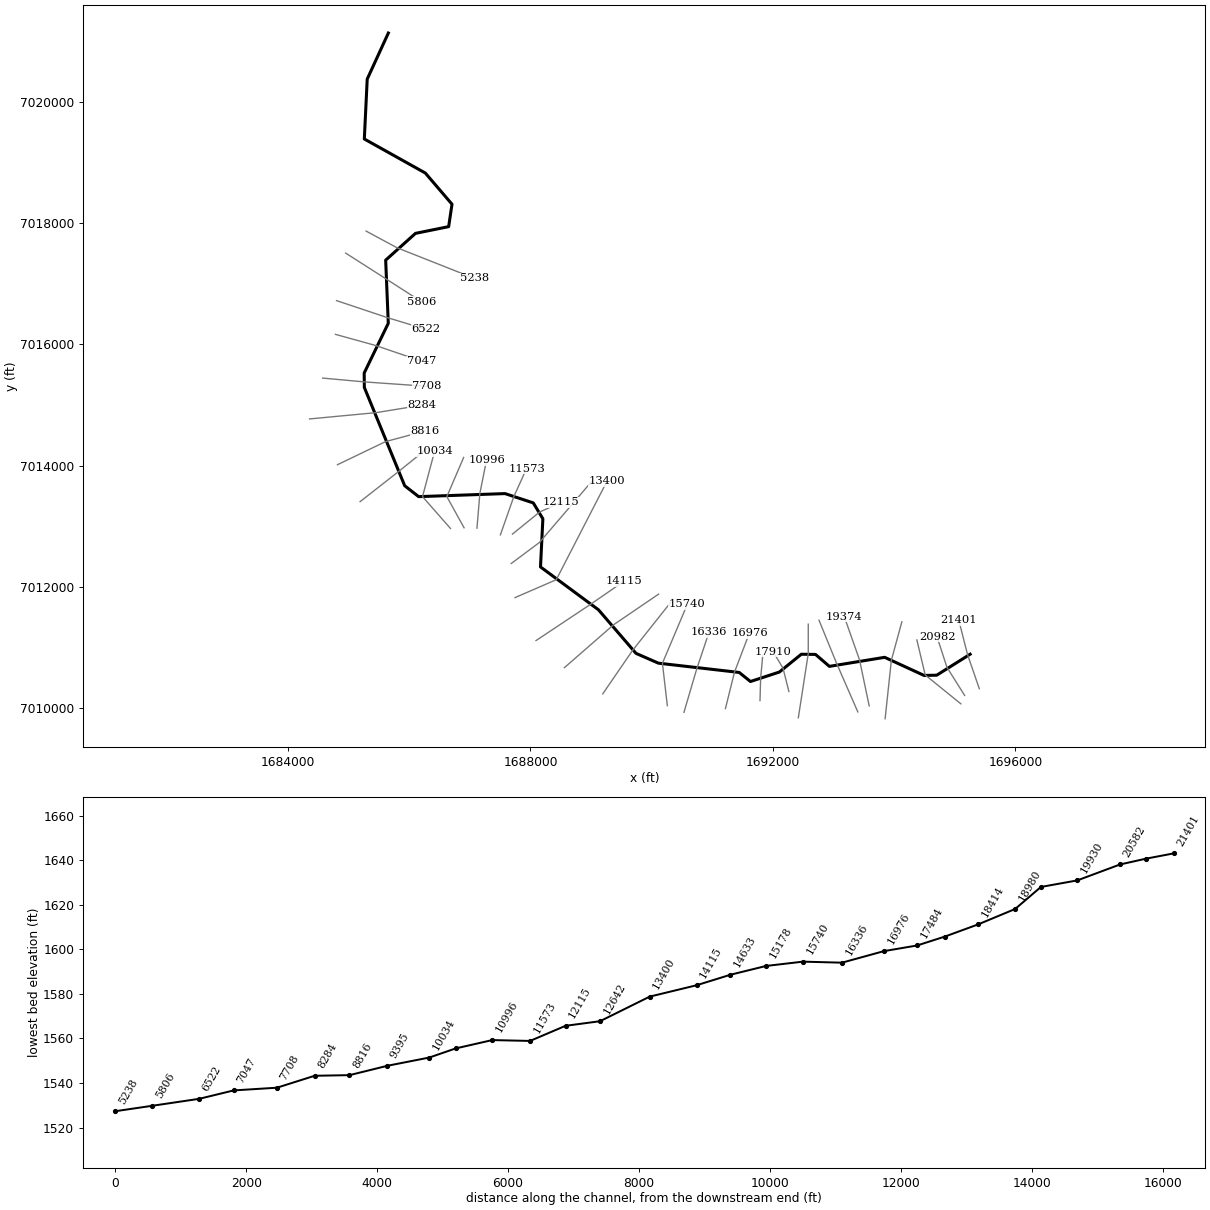
--- Chimney Creek 1178.prj (project) ---

Proj Title=Chimney Creek 1178 Base Level Engineering
Current Plan=p01
Default Exp/Contr=0.3,0.1
English Units
Geom File=g01
Flow File=f01
Plan File=p01
BEGIN DESCRIPTION:
Chimney Creek 1178
END DESCRIPTION:

--- Chimney Creek 1178.p01 (plan) ---

Plan Title=Multiple Run
Short Identifier=Multiple
Geom File=g01
Flow File=f01
Subcritical Flow
K Sum by GR= 0
Std Step Tol= 0.01
Critical Tol= 0.01
Num of Std Step Trials= 20
Max Error Tol= 0.3
Flow Tol Ratio= 0.001
Split Flow NTrial= 30
Split Flow Tol= 0.02
Split Flow Ratio= 0.02
Log Output Level= 0
Friction Slope Method= 1
Unsteady Friction Slope Method= 2
Unsteady Bridges Friction Slope Method= 1
Parabolic Critical Depth
Global Vel Dist=  1 , 1 , 1
Global Log Level= 0
CheckData=True
Encroach Param= -1, 0, 0, 0
BEGIN DESCRIPTION:
Multiple Run
END DESCRIPTION:

--- Chimney Creek 1178.f01 (steady flow) ---

Flow Title=Multiple
Number of Profiles=7
Profile Names=10-year,25-year,50-year,1pct_min,100-year,1pct_plu,500-year
River Rch & RM= Chimney Creek 11,Reach-1,21401
     263     364     449     275     549    1096     834
River Rch & RM= Chimney Creek 11,Reach-1,19930
     599     869    1104     697    1390    2774    2235
River Rch & RM= Chimney Creek 11,Reach-1,17910
     673     980    1247     789    1574    3140    2540
River Rch & RM= Chimney Creek 11,Reach-1,12115
     732    1070    1365     865    1726    3444    2798
River Rch & RM= Chimney Creek 11,Reach-1,9395
    1106    1636    2104    1341    2677    5341    4391
River Rch & RM= Chimney Creek 11,Reach-1,2053
    1105    1634    2099    1338    2669    5326    4373
Boundary for River Rch & Prof#=Chimney Creek 11,Reach-1,1
Up Type=0
Dn Type=3
Dn Slope=0.005
Boundary for River Rch & Prof#=Chimney Creek 11,Reach-1,2
Up Type=0
Dn Type=3
Dn Slope=0.005
Boundary for River Rch & Prof#=Chimney Creek 11,Reach-1,3
Up Type=0
Dn Type=3
Dn Slope=0.005
Boundary for River Rch & Prof#=Chimney Creek 11,Reach-1,4
Up Type=0
Dn Type=3
Dn Slope=0.005
Boundary for River Rch & Prof#=Chimney Creek 11,Reach-1,5
Up Type=0
Dn Type=3
Dn Slope=0.005
Boundary for River Rch & Prof#=Chimney Creek 11,Reach-1,6
Up Type=0
Dn Type=3
Dn Slope=0.005
Boundary for River Rch & Prof#=Chimney Creek 11,Reach-1,7
Up Type=0
Dn Type=3
Dn Slope=0.005

--- Chimney Creek 1178.g01 (geometry) ---

Geom Title=Existing Conditions

River Reach=Chimney Creek 11,Reach-1
Reach XY= 30
      1695255.00      7010888.00      1694703.45      7010541.75
      1694494.79      7010537.50      1693844.50      7010836.78
      1692932.21      7010687.41      1692703.54      7010884.46
      1692468.91      7010887.33      1692107.30      7010593.83
      1691629.96      7010437.50      1691444.57      7010586.95
      1690110.94      7010740.27      1689741.79      7010901.62
      1689121.67      7011621.35      1688165.48      7012328.20
      1688204.63      7013122.73      1688046.52      7013384.49
      1687580.08      7013538.20      1686155.00      7013488.00
      1685924.63      7013667.86      1685258.75      7015289.55
      1685256.22      7015527.50      1685653.95      7016348.44
      1685610.83      7017390.30      1686102.70      7017832.17
      1686649.97      7017943.07      1686705.32      7018313.11
      1686265.08      7018827.56      1685258.54      7019389.46
      1685306.22      7020377.50      1685655.00      7021138.00

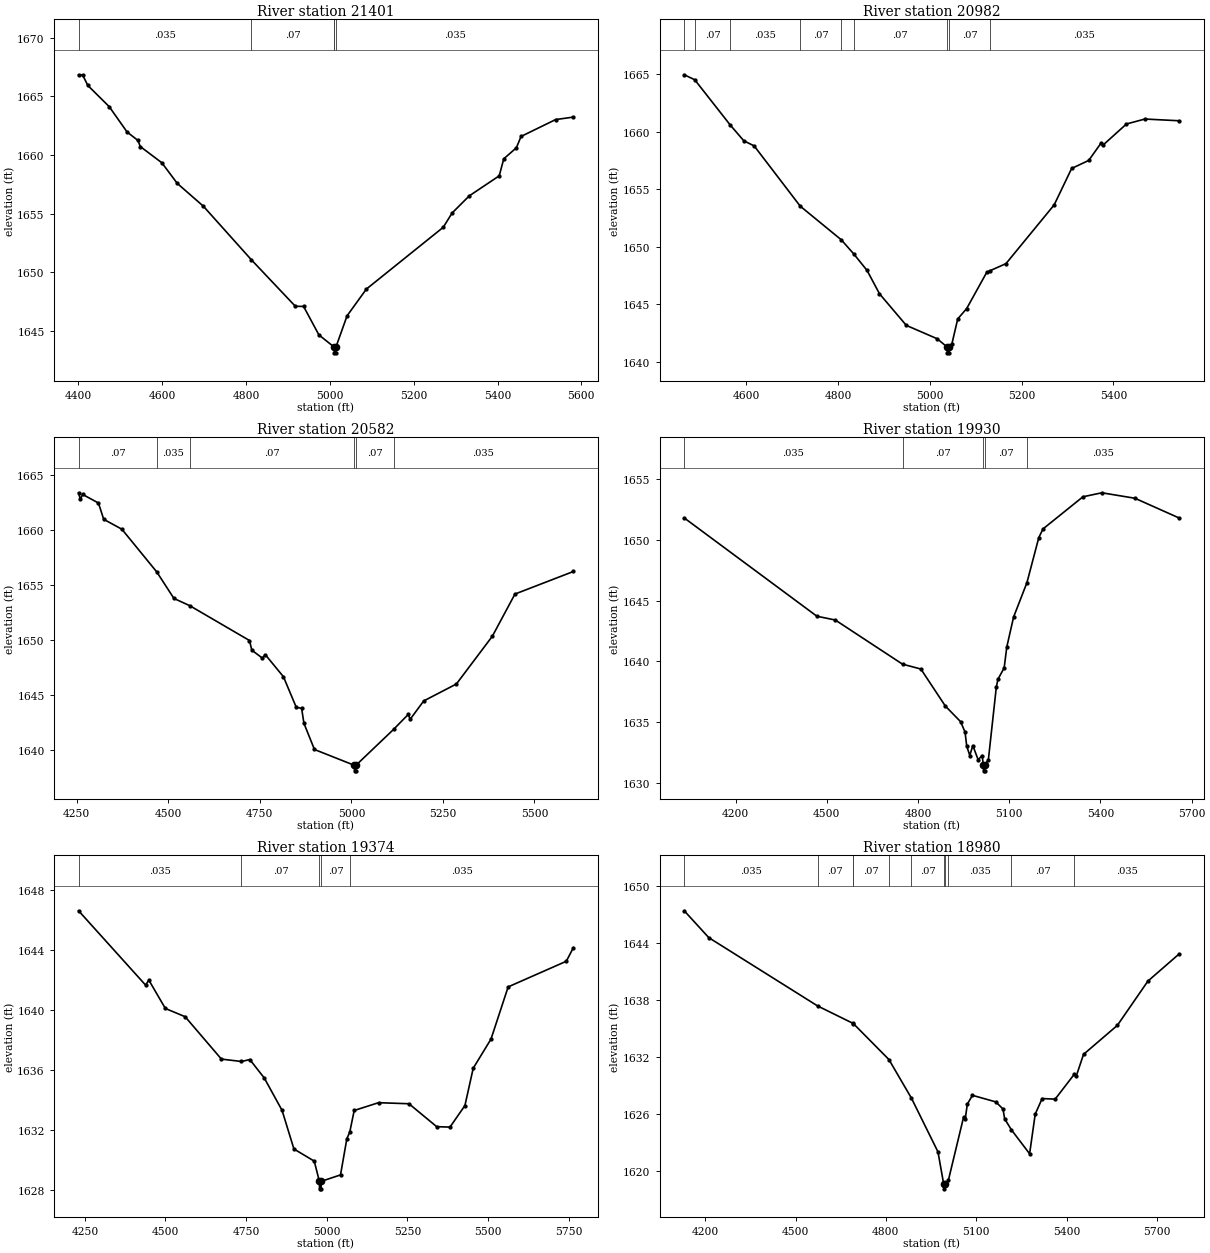
Type RM Length L Ch R = 1,21401,419,419,419
BEGIN DESCRIPTION:
Chimney Creek 1178 44.0
END DESCRIPTION:
XS GIS Cut Line= 3
      1695406.01      7010318.85      1695210.80      7010885.89
      1695067.47      7011449.03
#Sta/Elev= 30
  4400.3 1666.84  4410.0 1666.82  4422.3 1665.93  4473.4 1664.12  4516.0 1661.96
  4541.9 1661.24  4547.5 1660.72  4599.1 1659.33  4635.6 1657.58  4698.0 1655.63
  4812.3 1651.07  4917.6 1647.09  4937.2 1647.08  4973.8 1644.65  5009.9 1643.62
  5010.5 1643.62  5010.8 1643.12  5014.3 1643.12  5014.5 1643.62  5041.0 1646.28
  5087.1 1648.56  5270.5 1653.83  5291.7 1655.05  5332.6 1656.51  5404.1 1658.22
  5414.9 1659.67  5445.0 1660.61  5456.2 1661.58  5538.8 1663.02  5581.1 1663.23
#Mann=5,-1,0
  4400.3   0.035       0  4812.3    0.07       0  5009.9   0.035       0
  5010.5    0.07       0  5014.5   0.035       0
Bank Sta=5010.5,5014.5
Exp/Cntr=0.3,0.1

Type RM Length L Ch R = 1,20982,400,400,400
BEGIN DESCRIPTION:
Mapping XS 340ebca9
END DESCRIPTION:
XS GIS Cut Line= 3
      1695163.83      7010208.16      1694872.15      7010671.73
      1694708.08      7011176.96
#Sta/Elev= 30
  4464.4 1664.97  4487.2 1664.54  4564.7 1660.60  4594.2 1659.23  4616.9 1658.78
  4717.3 1653.54  4806.9 1650.61  4833.9 1649.39  4863.0 1647.95  4890.1 1645.92
  4948.6 1643.17  5016.2 1642.00  5037.7 1641.28  5038.0 1640.78  5041.5 1640.78
  5041.7 1641.28  5048.2 1641.59  5060.7 1643.73  5080.2 1644.63  5123.8 1647.77
  5130.9 1647.92  5165.9 1648.54  5271.0 1653.65  5309.1 1656.82  5346.4 1657.52
  5373.1 1659.02  5378.3 1658.88  5428.7 1660.69  5468.9 1661.12  5543.3 1660.97
#Mann=9,-1,0
  4464.4   0.035       0  4487.2    0.07       0  4564.7   0.035       0
  4717.3    0.07       0  4806.9   0.035       0  4833.9    0.07       0
  5037.7    0.07       0  5041.7    0.07       0  5130.9   0.035       0
Bank Sta=5037.7,5041.7
Exp/Cntr=0.3,0.1

Type RM Length L Ch R = 1,20582,652,652,652
BEGIN DESCRIPTION:
Mapping XS 5198fb06
END DESCRIPTION:
XS GIS Cut Line= 3
      1695102.15      7010068.89      1694513.64      7010545.43
      1694375.69      7011123.24
#Sta/Elev= 30
  4255.0 1663.41  4259.6 1662.82  4266.1 1663.26  4309.2 1662.48  4323.6 1661.00
  4373.2 1660.10  4468.5 1656.22  4515.4 1653.81  4558.8 1653.15  4721.7 1649.99
  4728.1 1649.11  4756.9 1648.39  4764.8 1648.71  4814.4 1646.70  4849.6 1643.91
  4864.0 1643.84  4870.4 1642.47  4899.1 1640.09  5008.3 1638.65  5008.6 1638.15
  5012.1 1638.15  5012.3 1638.65  5115.1 1641.91  5155.4 1643.28  5160.5 1642.83
  5197.5 1644.50  5286.8 1646.04  5385.0 1650.38  5446.7 1654.21  5606.3 1656.26
#Mann=6,-1,0
  4255.0    0.07       0  4468.5   0.035       0  4558.8    0.07       0
  5008.3    0.07       0  5012.3    0.07       0  5115.1   0.035       0
Bank Sta=5008.3,5012.3
Exp/Cntr=0.3,0.1

Type RM Length L Ch R = 1,19930,556,556,556
BEGIN DESCRIPTION:
Mapping XS 468c3f82
END DESCRIPTION:
XS GIS Cut Line= 3
      1693852.18      7009824.02      1693954.86      7010787.67
      1694128.23      7011423.04
#Sta/Elev= 30
  4030.9 1651.79  4467.3 1643.71  4527.7 1643.40  4748.9 1639.77  4809.3 1639.37
  4889.7 1636.33  4940.0 1635.04  4954.6 1634.19  4960.1 1633.04  4970.2 1632.26
  4980.2 1633.08  4997.7 1631.91  5010.7 1632.26  5014.9 1631.50  5015.4 1631.00
  5020.1 1631.00  5020.5 1631.50  5031.4 1631.92  5057.4 1637.86  5062.6 1638.52
  5083.3 1639.46  5092.0 1641.19  5114.4 1643.65  5158.2 1646.47  5197.3 1650.18
  5211.2 1650.89  5342.4 1653.53  5404.6 1653.86  5513.4 1653.41  5658.6 1651.79
#Mann=5,-1,0
  4030.9   0.035       0  4748.9    0.07       0  5014.9    0.07       0
  5020.5    0.07       0  5158.2   0.035       0
Bank Sta=5014.9,5020.5
Exp/Cntr=0.3,0.1

Type RM Length L Ch R = 1,19374,394,394,394
BEGIN DESCRIPTION:
Mapping XS a515fe6c
END DESCRIPTION:
XS GIS Cut Line= 3
      1693589.15      7010034.83      1693430.31      7010792.61
      1693177.71      7011508.72
#Sta/Elev= 30
  4230.7 1646.61  4438.3 1641.65  4448.5 1641.98  4499.6 1640.09  4560.9 1639.54
  4673.3 1636.71  4735.6 1636.55  4761.4 1636.68  4806.1 1635.45  4861.3 1633.29
  4898.1 1630.71  4961.1 1629.90  4977.0 1628.55  4977.4 1628.05  4982.2 1628.05
  4982.7 1628.55  5042.5 1628.98  5062.2 1631.40  5071.2 1631.84  5084.9 1633.28
  5160.3 1633.80  5254.6 1633.73  5340.6 1632.20  5381.8 1632.17  5428.1 1633.61
  5453.8 1636.10  5509.0 1638.05  5562.1 1641.53  5742.3 1643.24  5764.3 1644.15
#Mann=5,-1,0
  4230.7   0.035       0  4735.6    0.07       0  4977.0    0.07       0
  4982.7    0.07       0  5071.2   0.035       0
Bank Sta=4977,4982.7
Exp/Cntr=0.3,0.1

Type RM Length L Ch R = 1,18980,566,566,566
BEGIN DESCRIPTION:
Mapping XS 65976d34
END DESCRIPTION:
XS GIS Cut Line= 3
      1693401.66      7009935.84      1693050.10      7010740.52
      1692761.03      7011448.88
#Sta/Elev= 30
  4130.5 1647.41  4212.1 1644.58  4573.7 1637.39  4691.2 1635.56  4692.1 1635.54
  4810.1 1631.76  4884.7 1627.71  4973.1 1622.04  4992.1 1618.65  4992.6 1618.15
  4997.8 1618.65  5007.9 1619.08  5058.2 1625.70  5063.6 1625.51  5070.7 1627.07
  5087.6 1627.99  5165.1 1627.30  5189.1 1626.55  5194.5 1625.52  5217.0 1624.36
  5277.4 1621.84  5296.1 1626.02  5319.1 1627.65  5362.3 1627.59  5426.1 1630.22
  5432.4 1630.02  5456.5 1632.30  5568.8 1635.35  5670.3 1640.01  5773.7 1642.86
#Mann=11,-1,0
  4130.5   0.035       0  4573.7    0.07       0  4691.2   0.035       0
  4692.1    0.07       0  4810.1   0.035       0  4884.7    0.07       0
  4992.1    0.07       0  4997.8    0.07       0  5007.9   0.035       0
  5217.0    0.07       0  5426.1   0.035       0
Bank Sta=4992.1,4997.8
Exp/Cntr=0.3,0.1

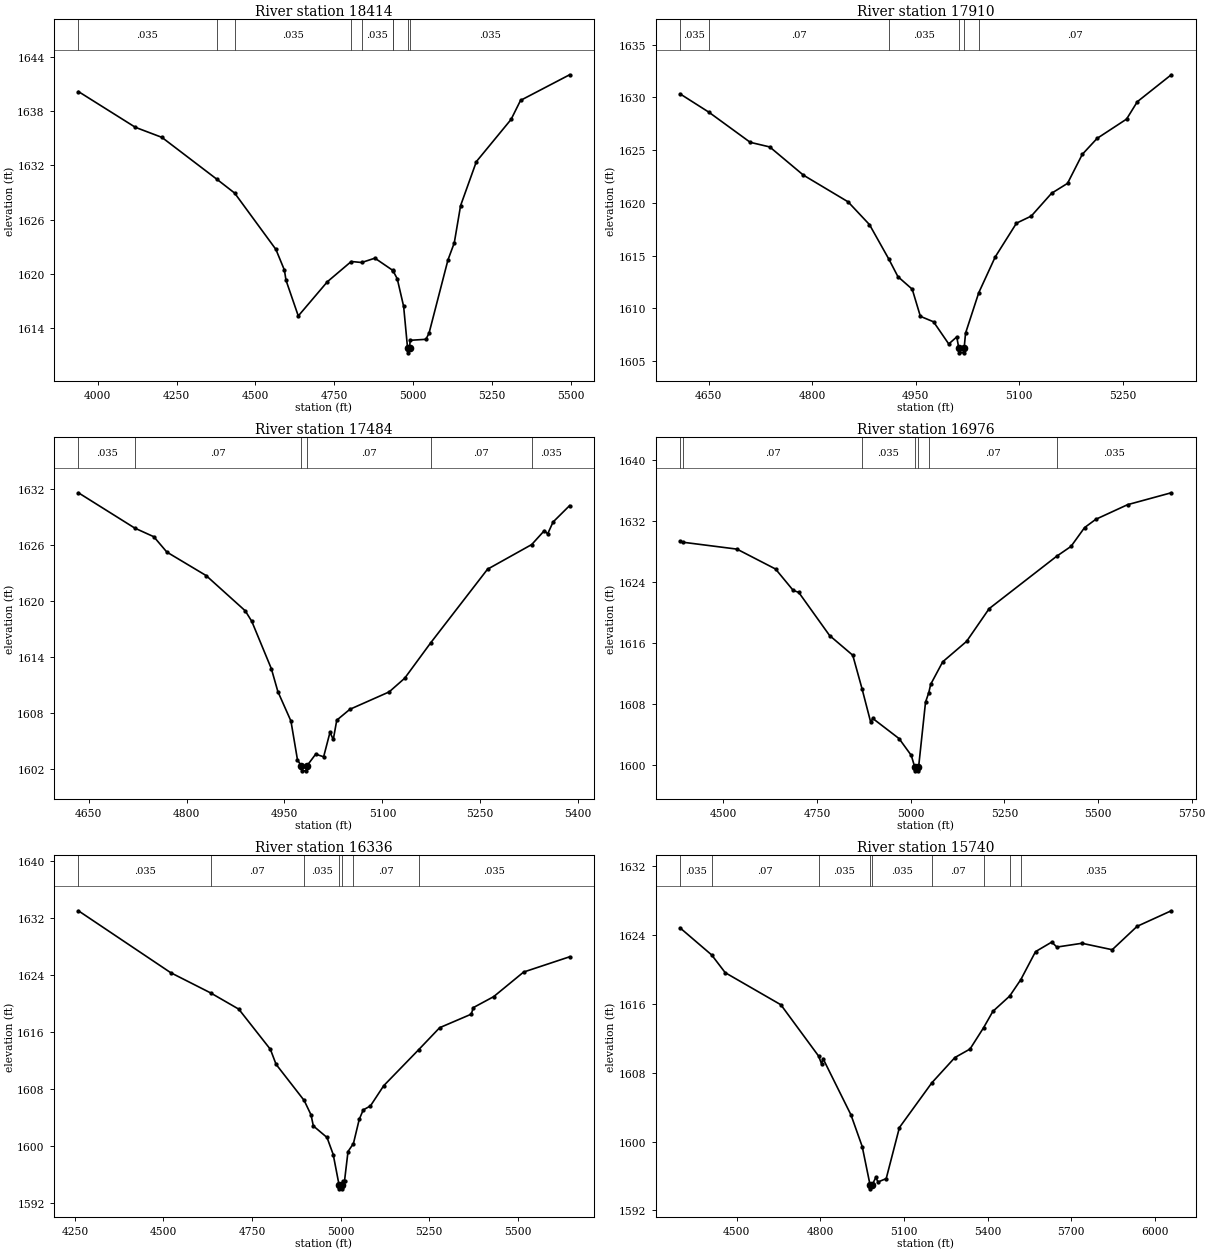
Type RM Length L Ch R = 1,18414,504,504,504
BEGIN DESCRIPTION:
Mapping XS 79f4322b
END DESCRIPTION:
XS GIS Cut Line= 3
      1692419.89      7009839.45      1692583.95      7010899.38
      1692583.95      7011383.42
#Sta/Elev= 30
  3938.9 1640.20  4119.6 1636.23  4203.4 1635.12  4376.7 1630.50  4434.0 1628.94
  4564.8 1622.69  4591.7 1620.40  4596.8 1619.27  4635.7 1615.31  4728.0 1619.11
  4803.6 1621.35  4836.7 1621.24  4878.5 1621.72  4934.6 1620.38  4936.1 1620.31
  4949.3 1619.44  4969.6 1616.37  4982.1 1611.72  4982.6 1611.22  4988.3 1611.72
  4990.2 1612.61  5040.1 1612.72  5050.1 1613.40  5110.1 1621.53  5130.1 1623.42
  5150.1 1627.55  5200.1 1632.43  5310.1 1637.11  5340.1 1639.22  5495.5 1642.06
#Mann=9,-1,0
  3938.9   0.035       0  4376.7    0.07       0  4434.0   0.035       0
  4803.6    0.07       0  4836.7   0.035       0  4934.6    0.07       0
  4936.1   0.035       0  4982.1   0.035       0  4988.3   0.035       0
Bank Sta=4982.1,4988.3
Exp/Cntr=0.3,0.1

Type RM Length L Ch R = 1,17910,426,426,426
BEGIN DESCRIPTION:
Mapping XS ce875e9c
END DESCRIPTION:
XS GIS Cut Line= 3
      1692264.25      7010272.06      1692167.03      7010657.48
      1692005.58      7010926.56
#Sta/Elev= 30
  4608.8 1630.33  4650.4 1628.60  4710.4 1625.74  4738.7 1625.30  4787.4 1622.63
  4852.1 1620.10  4883.1 1617.94  4911.3 1614.65  4924.3 1613.01  4945.0 1611.82
  4956.8 1609.25  4975.9 1608.73  4997.9 1606.63  5009.5 1607.30  5012.3 1606.29
  5012.8 1605.79  5019.8 1605.79  5020.3 1606.29  5022.2 1607.65  5041.3 1611.48
  5065.2 1614.88  5096.0 1618.08  5117.4 1618.75  5146.8 1620.91  5169.9 1621.85
  5191.3 1624.60  5212.7 1626.11  5255.4 1627.94  5271.0 1629.59  5320.1 1632.14
#Mann=6,-1,0
  4608.8   0.035       0  4650.4    0.07       0  4911.3   0.035       0
  5012.3   0.035       0  5020.3   0.035       0  5041.3    0.07       0
Bank Sta=5012.3,5020.3
Exp/Cntr=0.3,0.1

Type RM Length L Ch R = 1,17484,508,508,508
BEGIN DESCRIPTION:
Mapping XS e65666a0
END DESCRIPTION:
XS GIS Cut Line= 3
      1691787.40      7010122.51      1691797.81      7010488.79
      1691833.39      7010873.21
#Sta/Elev= 30
  4634.3 1631.64  4720.8 1627.84  4749.8 1626.92  4769.8 1625.27  4829.9 1622.75
  4889.9 1618.96  4899.9 1617.83  4929.9 1612.74  4939.9 1610.28  4959.9 1607.12
  4969.9 1602.96  4975.9 1602.27  4976.4 1601.77  4983.5 1601.77  4984.0 1602.27
  4997.8 1603.56  5010.0 1603.28  5019.7 1605.90  5024.8 1605.14  5030.1 1607.21
  5050.2 1608.38  5110.4 1610.25  5134.2 1611.72  5174.1 1615.53  5261.1 1623.43
  5328.8 1626.08  5348.2 1627.58  5353.2 1627.22  5361.5 1628.50  5386.8 1630.26
#Mann=6,-1,0
  4634.3   0.035       0  4720.8    0.07       0  4975.9   0.035       0
  4984.0    0.07       0  5174.1    0.07       0  5328.8   0.035       0
Bank Sta=4975.9,4984
Exp/Cntr=0.3,0.1

Type RM Length L Ch R = 1,16976,640,640,640
BEGIN DESCRIPTION:
Mapping XS 14902e07
END DESCRIPTION:
XS GIS Cut Line= 3
      1691217.15      7009990.58      1691365.59      7010589.55
      1691612.98      7011237.97
#Sta/Elev= 30
  4384.4 1629.33  4392.6 1629.20  4536.3 1628.30  4639.3 1625.69  4686.5 1622.88
  4701.1 1622.63  4783.5 1616.97  4845.4 1614.38  4870.0 1610.01  4893.4 1605.57
  4898.6 1606.10  4969.0 1603.45  5001.5 1601.25  5010.8 1599.72  5011.3 1599.22
  5018.4 1599.22  5018.9 1599.72  5021.2 1599.75  5039.6 1608.23  5048.3 1609.48
  5053.4 1610.57  5085.5 1613.52  5149.2 1616.20  5209.4 1620.49  5389.5 1627.36
  5428.0 1628.66  5464.1 1631.12  5494.1 1632.21  5579.0 1634.13  5695.5 1635.69
#Mann=7,-1,0
  4384.4   0.035       0  4392.6    0.07       0  4870.0   0.035       0
  5010.8   0.035       0  5018.9   0.035       0  5048.3    0.07       0
  5389.5   0.035       0
Bank Sta=5010.8,5018.9
Exp/Cntr=0.3,0.1

Type RM Length L Ch R = 1,16336,596,596,596
BEGIN DESCRIPTION:
Mapping XS 18bff09c
END DESCRIPTION:
XS GIS Cut Line= 3
      1690532.27      7009928.14      1690743.20      7010644.24
      1690946.33      7011251.02
#Sta/Elev= 30
  4260.0 1633.07  4520.5 1624.38  4633.2 1621.54  4712.7 1619.26  4801.9 1613.62
  4817.9 1611.52  4897.3 1606.44  4916.6 1604.42  4923.1 1602.87  4961.7 1601.25
  4979.2 1598.86  4995.9 1594.54  4996.4 1594.04  5004.0 1594.04  5004.5 1594.54
  5005.9 1595.13  5011.1 1595.13  5021.0 1599.28  5036.3 1600.40  5052.7 1603.80
  5064.0 1605.12  5084.3 1605.68  5121.8 1608.52  5220.6 1613.58  5279.7 1616.66
  5369.0 1618.56  5374.4 1619.47  5432.2 1621.02  5516.7 1624.47  5646.4 1626.61
#Mann=7,-1,0
  4260.0   0.035       0  4633.2    0.07       0  4897.3   0.035       0
  4995.9   0.035       0  5004.5   0.035       0  5036.3    0.07       0
  5220.6   0.035       0
Bank Sta=4995.9,5004.5
Exp/Cntr=0.3,0.1

Type RM Length L Ch R = 1,15740,562,562,562
BEGIN DESCRIPTION:
Mapping XS 4bdab1f2
END DESCRIPTION:
XS GIS Cut Line= 3
      1690258.17      7010038.79      1690177.44      7010739.29
      1690588.84      7011713.12
#Sta/Elev= 30
  4296.2 1624.85  4409.7 1621.70  4458.2 1619.64  4657.8 1615.91  4793.3 1609.94
  4804.0 1609.02  4809.1 1609.65  4909.4 1603.10  4949.7 1599.42  4977.6 1595.00
  4978.1 1594.50  4986.3 1595.00  4998.2 1595.82  5006.6 1595.30  5035.8 1595.69
  5083.2 1601.63  5199.7 1606.84  5282.2 1609.77  5336.5 1610.76  5385.0 1613.23
  5418.5 1615.14  5478.8 1616.92  5518.7 1618.83  5571.6 1622.09  5629.8 1623.20
  5648.1 1622.62  5738.1 1623.06  5846.7 1622.31  5936.0 1625.03  6058.5 1626.84
#Mann=9,-1,0
  4296.2   0.035       0  4409.7    0.07       0  4793.3   0.035       0
  4977.6   0.035       0  4986.3   0.035       0  5199.7    0.07       0
  5385.0   0.035       0  5478.8    0.07       0  5518.7   0.035       0
Bank Sta=4977.6,4986.3
Exp/Cntr=0.3,0.1

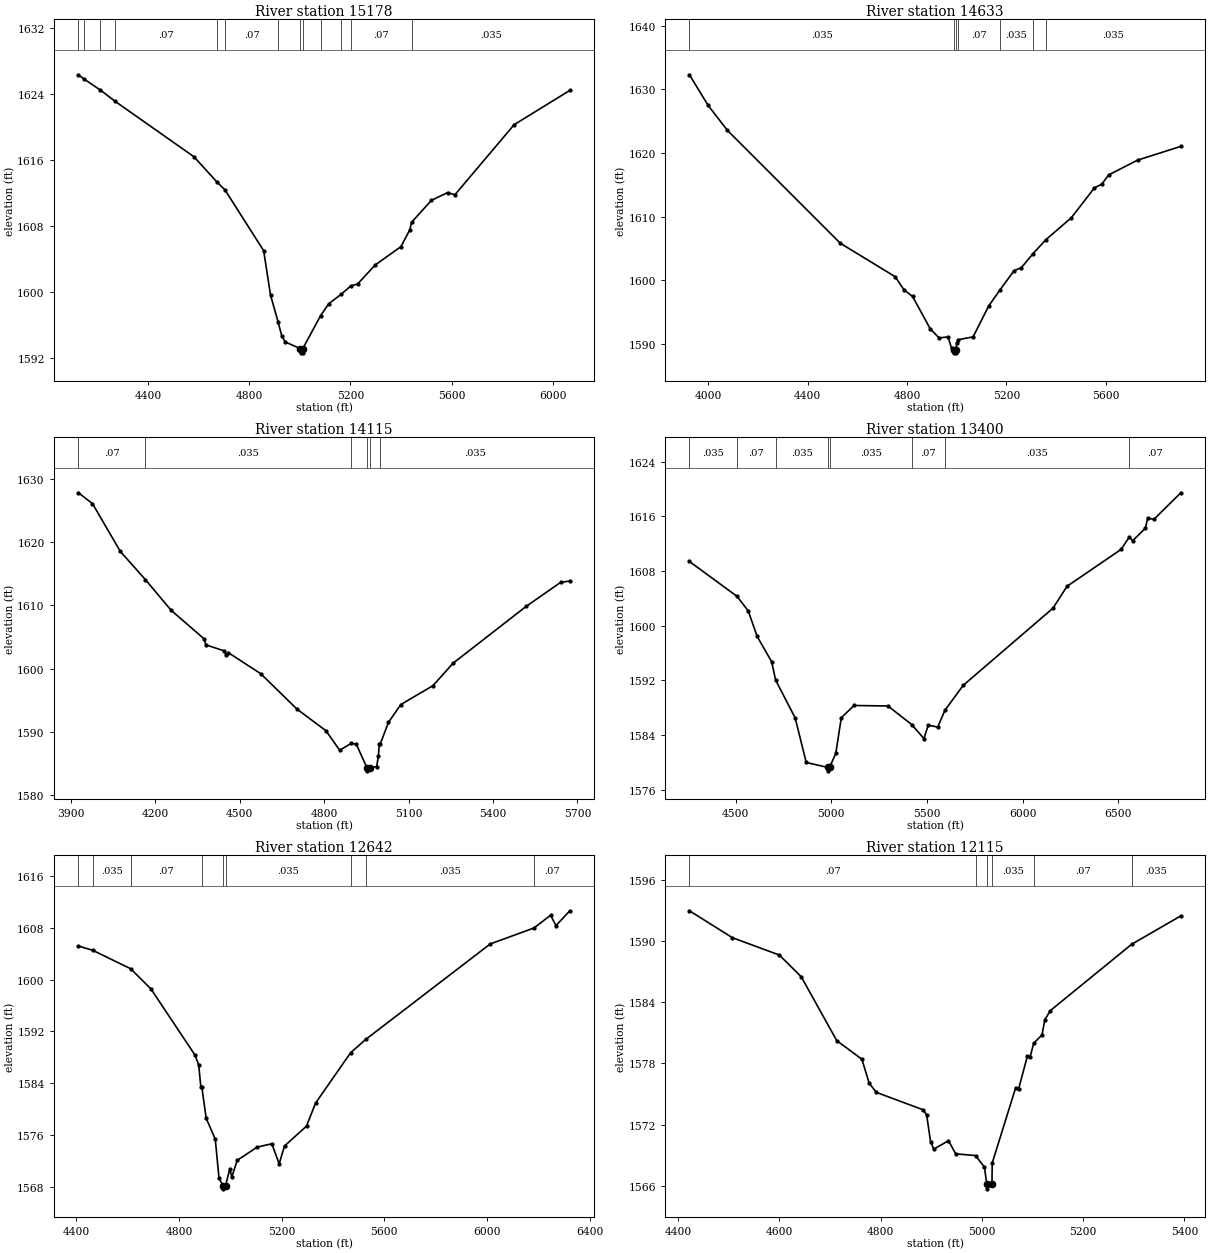
Type RM Length L Ch R = 1,15178,545,545,545
BEGIN DESCRIPTION:
Mapping XS 27e4f5cd
END DESCRIPTION:
XS GIS Cut Line= 3
      1689193.08      7010234.11      1689687.86      7010955.44
      1690350.98      7011790.19
#Sta/Elev= 30
  4125.6 1626.35  4148.9 1625.81  4212.0 1624.50  4269.8 1623.14  4582.4 1616.38
  4671.5 1613.36  4704.3 1612.37  4857.2 1604.98  4884.3 1599.59  4914.0 1596.35
  4929.0 1594.59  4942.8 1593.89  5002.4 1593.07  5002.9 1592.57  5010.9 1592.57
  5011.4 1593.07  5082.4 1597.10  5114.2 1598.53  5163.2 1599.68  5201.2 1600.70
  5228.0 1600.93  5298.4 1603.26  5399.4 1605.47  5434.6 1607.53  5441.4 1608.43
  5519.5 1611.09  5583.6 1612.04  5612.4 1611.77  5846.5 1620.29  6066.4 1624.45
#Mann=13,-1,0
  4125.6   0.035       0  4148.9    0.07       0  4212.0   0.035       0
  4269.8    0.07       0  4671.5   0.035       0  4704.3    0.07       0
  4914.0   0.035       0  5002.4   0.035       0  5011.4   0.035       0
  5082.4    0.07       0  5163.2   0.035       0  5201.2    0.07       0
  5441.4   0.035       0
Bank Sta=5002.4,5011.4
Exp/Cntr=0.3,0.1

Type RM Length L Ch R = 1,14633,518,518,518
BEGIN DESCRIPTION:
Mapping XS 5b2f0e5f
END DESCRIPTION:
XS GIS Cut Line= 3
      1688560.23      7010666.35      1689372.76      7011374.71
      1690114.97      7011879.94
#Sta/Elev= 30
  3925.2 1632.28  4000.3 1627.47  4078.2 1623.54  4532.0 1605.82  4752.2 1600.58
  4787.4 1598.54  4822.5 1597.47  4893.7 1592.37  4928.8 1590.97  4964.9 1591.12
  4979.1 1589.33  4988.3 1589.12  4988.8 1588.62  4997.0 1588.62  4997.5 1589.12
  5000.0 1590.16  5006.3 1590.68  5065.7 1591.13  5128.7 1596.00  5173.5 1598.48
  5230.4 1601.52  5259.9 1602.00  5305.0 1604.12  5358.1 1606.38  5460.8 1609.84
  5553.6 1614.53  5583.5 1615.11  5610.7 1616.56  5727.2 1618.88  5901.0 1621.04
#Mann=7,-1,0
  3925.2   0.035       0  4988.3   0.035       0  4997.5   0.035       0
  5006.3    0.07       0  5173.5   0.035       0  5305.0    0.07       0
  5358.1   0.035       0
Bank Sta=4988.3,4997.5
Exp/Cntr=0.3,0.1

Type RM Length L Ch R = 1,14115,715,715,715
BEGIN DESCRIPTION:
Mapping XS 49aea6f9
END DESCRIPTION:
XS GIS Cut Line= 3
      1688091.69      7011113.18      1688984.95      7011706.96
      1689539.66      7012089.79
#Sta/Elev= 30
  3926.3 1627.80  3976.2 1626.09  4075.4 1618.53  4164.1 1614.10  4255.8 1609.24
  4373.1 1604.73  4379.1 1603.79  4445.2 1602.82  4451.2 1602.13  4458.6 1602.57
  4574.5 1599.22  4703.8 1593.61  4806.0 1590.23  4854.9 1587.14  4896.6 1588.25
  4914.2 1588.08  4951.6 1584.39  4952.1 1583.89  4961.0 1584.39  4986.4 1584.56
  4992.4 1586.21  4995.9 1588.17  4999.5 1588.17  5028.2 1591.54  5071.9 1594.35
  5186.4 1597.34  5258.1 1600.89  5517.7 1609.86  5640.1 1613.65  5672.9 1613.87
#Mann=6,-1,0
  3926.3    0.07       0  4164.1   0.035       0  4896.6    0.07       0
  4951.6   0.035       0  4961.0    0.07       0  4999.5   0.035       0
Bank Sta=4951.6,4961
Exp/Cntr=0.3,0.1

Type RM Length L Ch R = 1,13400,758,758,758
BEGIN DESCRIPTION:
Mapping XS f2677f3a
END DESCRIPTION:
XS GIS Cut Line= 3
      1687745.19      7011821.99      1688425.71      7012117.11
      1689262.53      7013742.15
#Sta/Elev= 30
  4257.9 1609.39  4506.9 1604.29  4565.2 1602.17  4612.1 1598.43  4688.0 1594.72
  4708.4 1592.07  4810.8 1586.52  4868.6 1580.01  4981.2 1579.29  4981.7 1578.79
  4990.7 1579.29  5023.1 1581.34  5052.0 1586.55  5118.5 1588.34  5295.9 1588.27
  5420.8 1585.54  5484.1 1583.49  5506.3 1585.46  5556.3 1585.19  5593.8 1587.64
  5689.3 1591.28  6159.2 1602.57  6232.3 1605.76  6514.8 1611.15  6558.8 1612.99
  6575.4 1612.41  6642.2 1614.26  6654.1 1615.72  6686.6 1615.55  6827.5 1619.43
#Mann=8,-1,0
  4257.9   0.035       0  4506.9    0.07       0  4708.4   0.035       0
  4981.2   0.035       0  4990.7   0.035       0  5420.8    0.07       0
  5593.8   0.035       0  6558.8    0.07       0
Bank Sta=4981.2,4990.7
Exp/Cntr=0.3,0.1

Type RM Length L Ch R = 1,12642,527,527,527
BEGIN DESCRIPTION:
Mapping XS e36f5153
END DESCRIPTION:
XS GIS Cut Line= 3
      1687682.66      7012384.48      1688147.93      7012731.70
      1689014.89      7013744.31
#Sta/Elev= 30
  4408.6 1605.17  4464.2 1604.51  4612.3 1601.66  4691.3 1598.54  4862.3 1588.38
  4876.9 1586.86  4885.2 1583.50  4889.2 1583.43  4906.1 1578.63  4941.5 1575.40
  4956.1 1569.37  4972.1 1568.25  4972.6 1567.75  4981.7 1568.25  4998.2 1570.86
  5005.9 1569.54  5026.7 1572.14  5104.7 1574.18  5161.7 1574.70  5190.3 1571.60
  5211.1 1574.35  5296.8 1577.42  5331.9 1580.96  5468.5 1588.72  5527.2 1590.77
  6012.4 1605.49  6182.9 1607.95  6247.3 1609.92  6268.2 1608.31  6322.2 1610.60
#Mann=9,-1,0
  4408.6    0.07       0  4464.2   0.035       0  4612.3    0.07       0
  4889.2   0.035       0  4972.1   0.035       0  4981.7   0.035       0
  5468.5    0.07       0  5527.2   0.035       0  6182.9    0.07       0
Bank Sta=4972.1,4981.7
Exp/Cntr=0.3,0.1

Type RM Length L Ch R = 1,12115,542,542,542
BEGIN DESCRIPTION:
Mapping XS 37bee559
END DESCRIPTION:
XS GIS Cut Line= 3
      1687703.07      7012870.26      1688152.30      7013234.85
      1688510.19      7013395.36
#Sta/Elev= 30
  4422.2 1593.01  4507.2 1590.36  4599.8 1588.66  4643.0 1586.53  4713.3 1580.24
  4762.9 1578.42  4777.3 1576.06  4791.6 1575.16  4884.3 1573.44  4890.8 1572.94
  4898.7 1570.27  4905.1 1569.59  4933.9 1570.41  4948.3 1569.12  4987.4 1568.95
  5005.0 1567.81  5009.5 1566.18  5010.0 1565.68  5019.8 1566.18  5020.4 1568.22
  5066.8 1575.64  5072.3 1575.46  5090.0 1578.75  5095.4 1578.68  5102.3 1579.99
  5118.6 1580.80  5124.3 1582.30  5135.2 1583.20  5295.9 1589.72  5393.0 1592.51
#Mann=6,-1,0
  4422.2    0.07       0  4987.4   0.035       0  5009.5   0.035       0
  5019.8   0.035       0  5102.3    0.07       0  5295.9   0.035       0
Bank Sta=5009.5,5019.8
Exp/Cntr=0.3,0.1

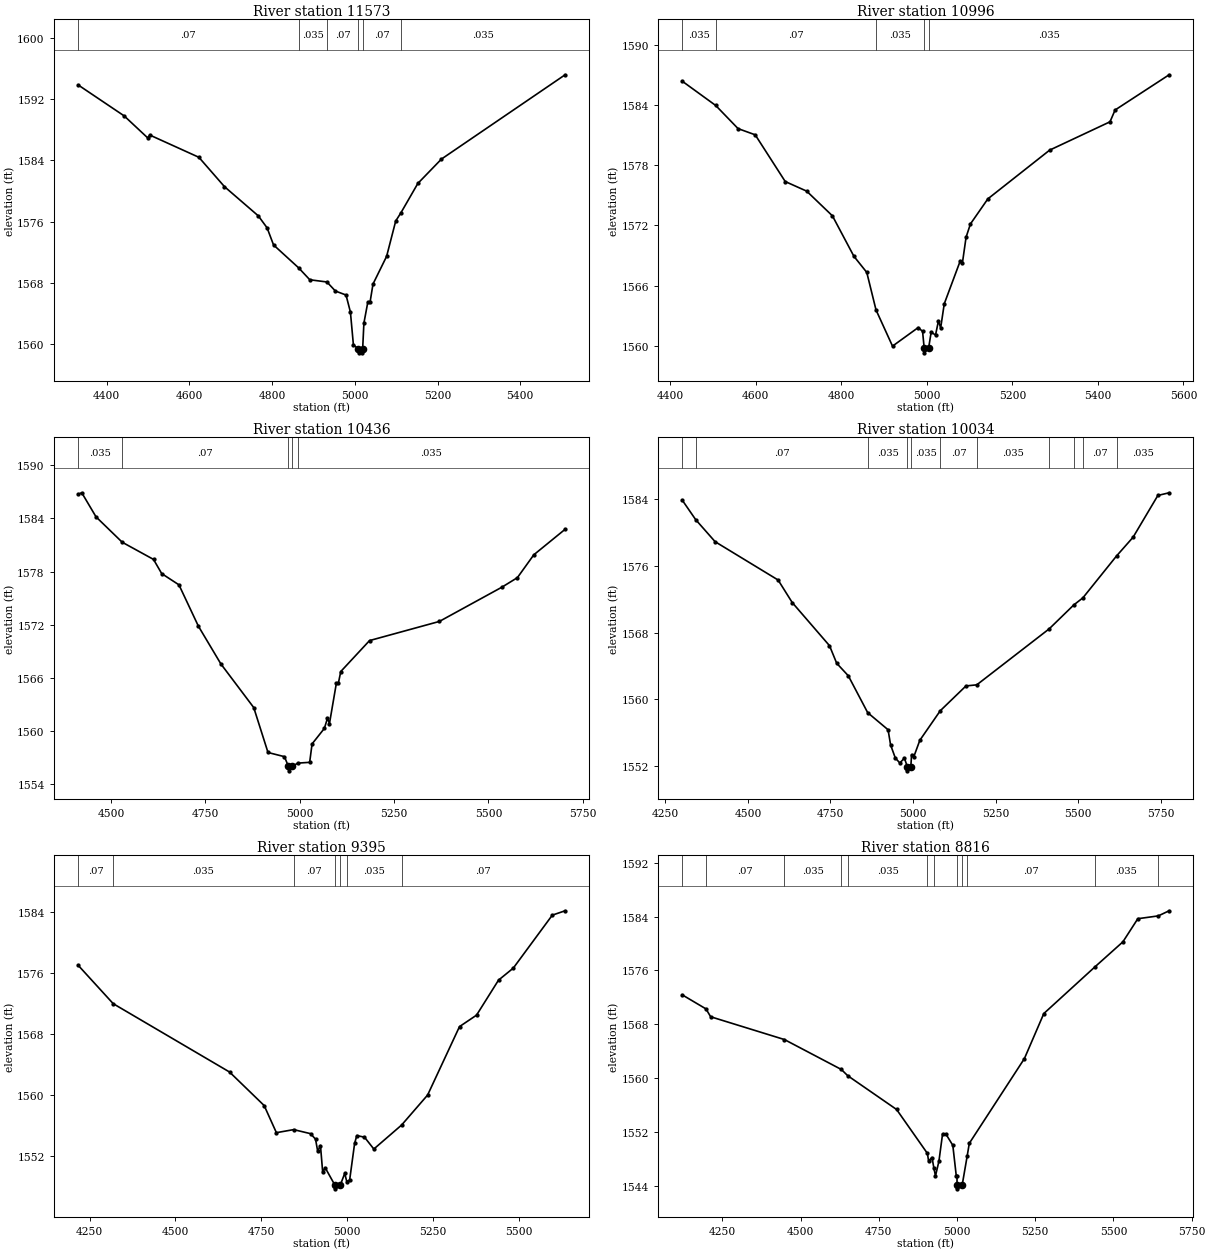
Type RM Length L Ch R = 1,11573,577,577,577
BEGIN DESCRIPTION:
Mapping XS e536b0ff
END DESCRIPTION:
XS GIS Cut Line= 3
      1687503.44      7012857.28      1687724.78      7013486.59
      1687935.29      7013951.00
#Sta/Elev= 30
  4331.4 1593.82  4442.5 1589.79  4499.2 1586.93  4504.5 1587.29  4623.1 1584.39
  4685.0 1580.56  4766.8 1576.75  4788.0 1575.19  4803.6 1572.96  4864.3 1569.97
  4891.2 1568.42  4932.6 1568.13  4953.1 1566.95  4978.8 1566.43  4989.4 1564.21
  4996.6 1559.94  5008.6 1559.39  5009.1 1558.89  5018.5 1558.89  5019.0 1559.39
  5022.0 1562.76  5031.4 1565.48  5036.9 1565.50  5044.0 1567.86  5076.9 1571.47
  5098.9 1576.08  5111.7 1577.17  5152.4 1580.98  5209.5 1584.16  5508.4 1595.15
#Mann=6,-1,0
  4331.4    0.07       0  4864.3   0.035       0  4932.6    0.07       0
  5008.6    0.07       0  5019.0    0.07       0  5111.7   0.035       0
Bank Sta=5008.6,5019
Exp/Cntr=0.3,0.1

Type RM Length L Ch R = 1,10996,560,560,560
BEGIN DESCRIPTION:
Mapping XS ce0ab268
END DESCRIPTION:
XS GIS Cut Line= 3
      1687117.14      7012967.89      1687164.89      7013540.84
      1687275.45      7014093.65
#Sta/Elev= 30
  4427.9 1586.42  4506.3 1583.99  4558.5 1581.68  4598.6 1581.06  4668.8 1576.39
  4719.0 1575.43  4779.2 1572.96  4829.4 1568.92  4859.5 1567.31  4881.1 1563.56
  4919.7 1559.94  4979.9 1561.80  4990.0 1561.41  4993.7 1559.77  4994.2 1559.27
  5004.2 1559.77  5010.1 1561.34  5020.3 1561.05  5027.2 1562.48  5032.3 1561.76
  5040.7 1564.17  5078.2 1568.47  5083.3 1568.29  5091.7 1570.82  5101.9 1572.15
  5142.7 1574.66  5287.2 1579.53  5428.3 1582.36  5440.2 1583.54  5566.6 1587.06
#Mann=5,-1,0
  4427.9   0.035       0  4506.3    0.07       0  4881.1   0.035       0
  4993.7   0.035       0  5004.2   0.035       0
Bank Sta=4993.7,5004.2
Exp/Cntr=0.3,0.1

Type RM Length L Ch R = 1,10436,402,402,402
BEGIN DESCRIPTION:
Chimney Creek 1178 21.0
END DESCRIPTION:
XS GIS Cut Line= 3
      1686904.48      7012974.41      1686620.01      7013487.98
      1686897.44      7014134.25
#Sta/Elev= 30
  4412.9 1586.73  4422.4 1586.89  4460.2 1584.17  4529.5 1581.31  4612.5 1579.37
  4634.2 1577.77  4679.9 1576.50  4731.5 1571.83  4791.1 1567.57  4878.1 1562.65
  4915.9 1557.58  4959.4 1557.11  4970.1 1556.01  4970.6 1555.51  4980.7 1556.01
  4994.5 1556.38  5026.3 1556.47  5032.7 1558.55  5065.3 1560.30  5073.4 1561.43
  5078.8 1560.85  5097.0 1565.38  5102.4 1565.41  5108.8 1566.72  5185.0 1570.21
  5370.0 1572.37  5535.5 1576.23  5576.8 1577.31  5620.3 1579.89  5703.3 1582.77
#Mann=5,-1,0
  4412.9   0.035       0  4529.5    0.07       0  4970.1   0.035       0
  4980.7    0.07       0  4994.5   0.035       0
Bank Sta=4970.1,4980.7
Exp/Cntr=0.3,0.1

Type RM Length L Ch R = 1,10034,639,639,639
BEGIN DESCRIPTION:
Chimney Creek 1178 20.0
END DESCRIPTION:
XS GIS Cut Line= 3
      1686680.02      7012962.98      1686218.70      7013488.00
      1686418.36      7014237.46
#Sta/Elev= 30
  4301.1 1583.91  4342.0 1581.56  4400.7 1578.92  4591.5 1574.32  4634.2 1571.62
  4747.1 1566.44  4768.9 1564.33  4804.0 1562.83  4862.8 1558.40  4924.5 1556.35
  4932.1 1554.53  4946.3 1552.97  4960.1 1552.36  4973.9 1552.95  4982.8 1551.92
  4983.3 1551.42  4993.4 1551.92  4995.7 1553.37  5002.5 1553.12  5020.7 1555.09
  5082.5 1558.63  5160.4 1561.61  5193.1 1561.74  5412.4 1568.46  5486.9 1571.33
  5514.4 1572.18  5616.4 1577.21  5666.5 1579.46  5741.5 1584.47  5775.6 1584.79
#Mann=11,-1,0
  4301.1   0.035       0  4342.0    0.07       0  4862.8   0.035       0
  4982.8   0.035       0  4993.4   0.035       0  5082.5    0.07       0
  5193.1   0.035       0  5412.4    0.07       0  5486.9   0.035       0
  5514.4    0.07       0  5616.4   0.035       0
Bank Sta=4982.8,4993.4
Exp/Cntr=0.3,0.1

Type RM Length L Ch R = 1,9395,579,579,579
BEGIN DESCRIPTION:
Mapping XS 95e85edd
END DESCRIPTION:
XS GIS Cut Line= 3
      1685188.43      7013404.91      1685806.91      7013888.85
      1686299.55      7014286.00
#Sta/Elev= 30
  4216.7 1576.98  4318.7 1571.96  4657.4 1563.02  4758.3 1558.63  4793.9 1555.08
  4844.3 1555.48  4893.4 1554.95  4907.9 1554.23  4914.2 1552.65  4922.3 1553.40
  4928.7 1549.92  4936.1 1550.49  4964.1 1548.23  4964.6 1547.73  4980.1 1548.23
  4992.9 1549.75  4998.9 1548.68  5007.3 1548.89  5021.7 1553.67  5028.1 1554.70
  5050.5 1554.49  5077.7 1552.94  5158.6 1556.08  5234.4 1560.01  5327.2 1568.96
  5376.8 1570.46  5440.8 1575.04  5483.9 1576.62  5597.5 1583.55  5634.8 1584.12
#Mann=7,-1,0
  4216.7    0.07       0  4318.7   0.035       0  4844.3    0.07       0
  4964.1   0.035       0  4980.1    0.07       0  4998.9   0.035       0
  5158.6    0.07       0
Bank Sta=4964.1,4980.1
Exp/Cntr=0.3,0.1

Type RM Length L Ch R = 1,8816,532,532,532
BEGIN DESCRIPTION:
Mapping XS f749eb2a
END DESCRIPTION:
XS GIS Cut Line= 3
      1684815.34      7014014.92      1685607.04      7014395.15
      1686261.65      7014571.79
#Sta/Elev= 30
  4121.7 1572.37  4197.6 1570.28  4212.6 1569.11  4448.4 1565.72  4630.3 1561.27
  4650.8 1560.34  4806.9 1555.32  4905.5 1548.78  4909.0 1547.68  4920.1 1548.18
  4926.0 1546.63  4931.2 1545.44  4942.2 1547.63  4953.9 1551.71  4964.4 1551.67
  4986.6 1549.99  4997.5 1545.50  5000.0 1545.50  5000.1 1544.02  5000.6 1543.52
  5016.3 1544.02  5032.4 1548.37  5039.3 1550.29  5215.4 1562.89  5277.5 1569.59
  5439.7 1576.48  5530.2 1580.25  5577.9 1583.69  5643.4 1584.11  5678.0 1584.87
#Mann=12,-1,0
  4121.7   0.035       0  4197.6    0.07       0  4448.4   0.035       0
  4630.3    0.07       0  4650.8   0.035       0  4905.5    0.07       0
  4926.0   0.035       0  5000.1   0.035       0  5016.3   0.035       0
  5032.4    0.07       0  5439.7   0.035       0  5643.4    0.07       0
Bank Sta=5000.1,5016.3
Exp/Cntr=0.3,0.1

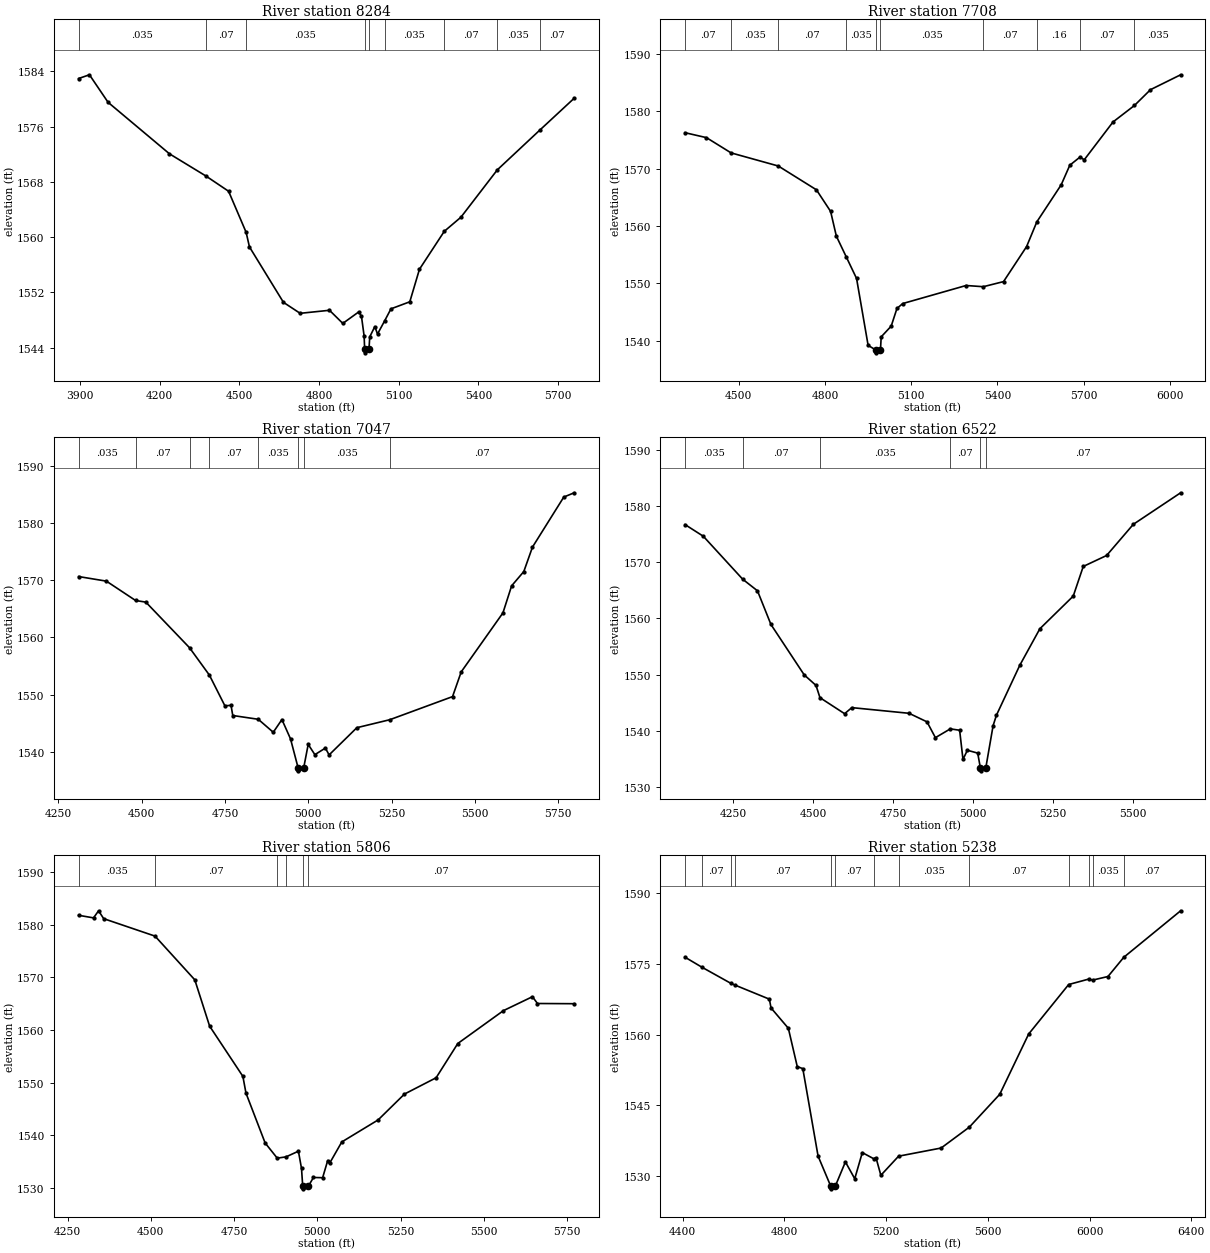
Type RM Length L Ch R = 1,8284,576,576,576
BEGIN DESCRIPTION:
Mapping XS a7e7cdd1
END DESCRIPTION:
XS GIS Cut Line= 3
      1684354.45      7014770.15      1685456.00      7014874.31
      1686206.01      7014996.71
#Sta/Elev= 30
  3894.5 1582.95  3935.2 1583.49  4005.5 1579.50  4236.6 1572.05  4373.4 1568.85
  4459.3 1566.63  4525.3 1560.69  4537.9 1558.57  4665.9 1550.55  4728.8 1548.96
  4839.3 1549.40  4889.5 1547.50  4949.7 1549.17  4959.8 1548.52  4969.8 1545.67
  4971.8 1543.74  4972.3 1543.24  4988.0 1543.74  4991.0 1545.56  5010.1 1547.04
  5020.2 1545.96  5047.2 1547.88  5070.9 1549.61  5141.8 1550.63  5178.2 1555.34
  5271.7 1560.83  5334.3 1562.87  5471.5 1569.73  5630.9 1575.46  5760.9 1580.09
#Mann=9,-1,0
  3894.5   0.035       0  4373.4    0.07       0  4525.3   0.035       0
  4971.8    0.07       0  4988.0   0.035       0  5047.2   0.035       0
  5271.7    0.07       0  5471.5   0.035       0  5630.9    0.07       0
Bank Sta=4971.8,4988
Exp/Cntr=0.3,0.1

Type RM Length L Ch R = 1,7708,661,661,661
BEGIN DESCRIPTION:
Mapping XS 34340c9f
END DESCRIPTION:
XS GIS Cut Line= 3
      1684570.87      7015444.45      1685250.53      7015381.95
      1686289.64      7015309.03
#Sta/Elev= 30
  4313.1 1576.29  4387.5 1575.43  4473.1 1572.77  4637.4 1570.48  4770.0 1566.33
  4819.4 1562.56  4839.4 1558.24  4873.6 1554.65  4909.7 1550.86  4949.9 1539.19
  4976.4 1538.38  4976.9 1537.88  4992.9 1538.38  4995.4 1540.67  5030.2 1542.54
  5050.2 1545.62  5070.3 1546.48  5290.8 1549.63  5350.7 1549.42  5421.1 1550.31
  5501.3 1556.42  5537.0 1560.74  5621.6 1567.19  5651.7 1570.62  5687.4 1572.05
  5701.8 1571.56  5802.1 1578.17  5876.5 1581.04  5932.4 1583.80  6037.3 1586.40
#Mann=10,-1,0
  4313.1    0.07       0  4473.1   0.035       0  4637.4    0.07       0
  4873.6   0.035       0  4976.4   0.035       0  4992.9   0.035       0
  5350.7    0.07       0  5537.0    0.16       0  5687.4    0.07       0
  5876.5   0.035       0
Bank Sta=4976.4,4992.9
Exp/Cntr=0.3,0.1

Type RM Length L Ch R = 1,7047,525,525,525
BEGIN DESCRIPTION:
Mapping XS e03508a0
END DESCRIPTION:
XS GIS Cut Line= 3
      1684781.81      7016165.80      1685440.64      7015983.51
      1686201.84      7015723.72
#Sta/Elev= 30
  4310.5 1570.61  4393.8 1569.81  4481.4 1566.43  4512.3 1566.14  4643.5 1558.17
  4703.1 1553.39  4749.6 1548.03  4768.1 1548.10  4773.3 1546.33  4849.8 1545.67
  4894.9 1543.40  4920.9 1545.62  4946.7 1542.25  4969.6 1537.16  4970.1 1536.66
  4986.2 1537.16  4999.8 1541.28  5019.8 1539.49  5051.5 1540.64  5062.5 1539.44
  5145.9 1544.20  5244.6 1545.59  5433.2 1549.63  5459.2 1553.95  5584.5 1564.26
  5610.6 1568.99  5647.2 1571.49  5673.2 1575.76  5767.2 1584.50  5798.4 1585.25
#Mann=8,-1,0
  4310.5   0.035       0  4481.4    0.07       0  4643.5   0.035       0
  4703.1    0.07       0  4849.8   0.035       0  4969.6   0.035       0
  4986.2   0.035       0  5244.6    0.07       0
Bank Sta=4969.6,4986.2
Exp/Cntr=0.3,0.1

Type RM Length L Ch R = 1,6522,716,716,716
BEGIN DESCRIPTION:
Mapping XS b9e7d8f3
END DESCRIPTION:
XS GIS Cut Line= 3
      1684800.17      7016722.48      1685649.12      7016438.63
      1686276.71      7016248.52
#Sta/Elev= 30
  4098.6 1576.67  4155.6 1574.60  4278.9 1566.96  4325.1 1564.90  4367.3 1558.91
  4471.4 1549.95  4508.3 1548.08  4520.7 1545.90  4597.8 1543.05  4620.4 1544.13
  4799.6 1543.12  4855.7 1541.60  4882.0 1538.79  4928.6 1540.35  4957.8 1540.11
  4968.3 1534.92  4982.0 1536.55  5014.4 1536.04  5022.8 1533.39  5023.3 1532.89
  5039.6 1533.39  5062.6 1540.93  5073.0 1542.78  5146.0 1551.65  5208.9 1558.15
  5313.4 1563.96  5344.7 1569.23  5417.8 1571.18  5501.4 1576.72  5649.5 1582.33
#Mann=6,-1,0
  4098.6   0.035       0  4278.9    0.07       0  4520.7   0.035       0
  4928.6    0.07       0  5022.8    0.07       0  5039.6    0.07       0
Bank Sta=5022.8,5039.6
Exp/Cntr=0.3,0.1

Type RM Length L Ch R = 1,5806,568,568,568
BEGIN DESCRIPTION:
Mapping XS 20148ff3
END DESCRIPTION:
XS GIS Cut Line= 3
      1684951.17      7017506.35      1685550.16      7017123.52
      1686203.78      7016704.27
#Sta/Elev= 30
  4283.4 1581.81  4328.1 1581.32  4343.3 1582.67  4358.6 1581.17  4512.7 1577.85
  4632.1 1569.53  4676.6 1560.72  4776.4 1551.17  4785.7 1547.98  4843.2 1538.50
  4879.5 1535.61  4905.8 1535.85  4943.1 1536.93  4952.4 1533.64  4956.0 1530.27
  4956.5 1529.77  4972.9 1530.27  4988.2 1531.93  5015.8 1531.89  5031.0 1535.15
  5036.9 1534.65  5073.3 1538.69  5182.3 1542.88  5261.4 1547.80  5356.4 1550.90
  5421.5 1557.42  5558.4 1563.67  5645.5 1566.32  5660.7 1565.03  5770.8 1564.99
#Mann=6,-1,0
  4283.4   0.035       0  4512.7    0.07       0  4879.5   0.035       0
  4905.8    0.07       0  4956.0    0.07       0  4972.9    0.07       0
Bank Sta=4956,4972.9
Exp/Cntr=0.3,0.1

Type RM Length L Ch R = 1,5238,1103,1103,1103
BEGIN DESCRIPTION:
Mapping XS dd66f415
END DESCRIPTION:
XS GIS Cut Line= 3
      1685287.47      7017869.71      1685799.65      7017594.08
      1687070.63      7017090.89
#Sta/Elev= 30
  4409.6 1576.39  4475.1 1574.30  4589.3 1570.87  4604.9 1570.51  4741.0 1567.51
  4747.5 1565.65  4815.6 1561.34  4850.6 1553.23  4872.5 1552.78  4932.5 1534.25
  4982.8 1527.81  4983.3 1527.31  4999.7 1527.81  5040.0 1533.02  5076.7 1529.45
  5106.4 1534.99  5150.6 1533.71  5160.4 1533.88  5179.4 1530.18  5249.1 1534.23
  5416.4 1535.96  5527.4 1540.39  5646.9 1547.35  5760.6 1560.12  5917.9 1570.61
  5995.9 1571.75  6012.4 1571.55  6072.5 1572.31  6134.6 1576.38  6358.2 1586.24
#Mann=13,-1,0
  4409.6   0.035       0  4475.1    0.07       0  4589.3   0.035       0
  4604.9    0.07       0  4982.8   0.035       0  4999.7    0.07       0
  5150.6    0.07       0  5249.1   0.035       0  5527.4    0.07       0
  5917.9   0.035       0  5995.9    0.07       0  6012.4   0.035       0
  6134.6    0.07       0
Bank Sta=4982.8,4999.7
Exp/Cntr=0.3,0.1