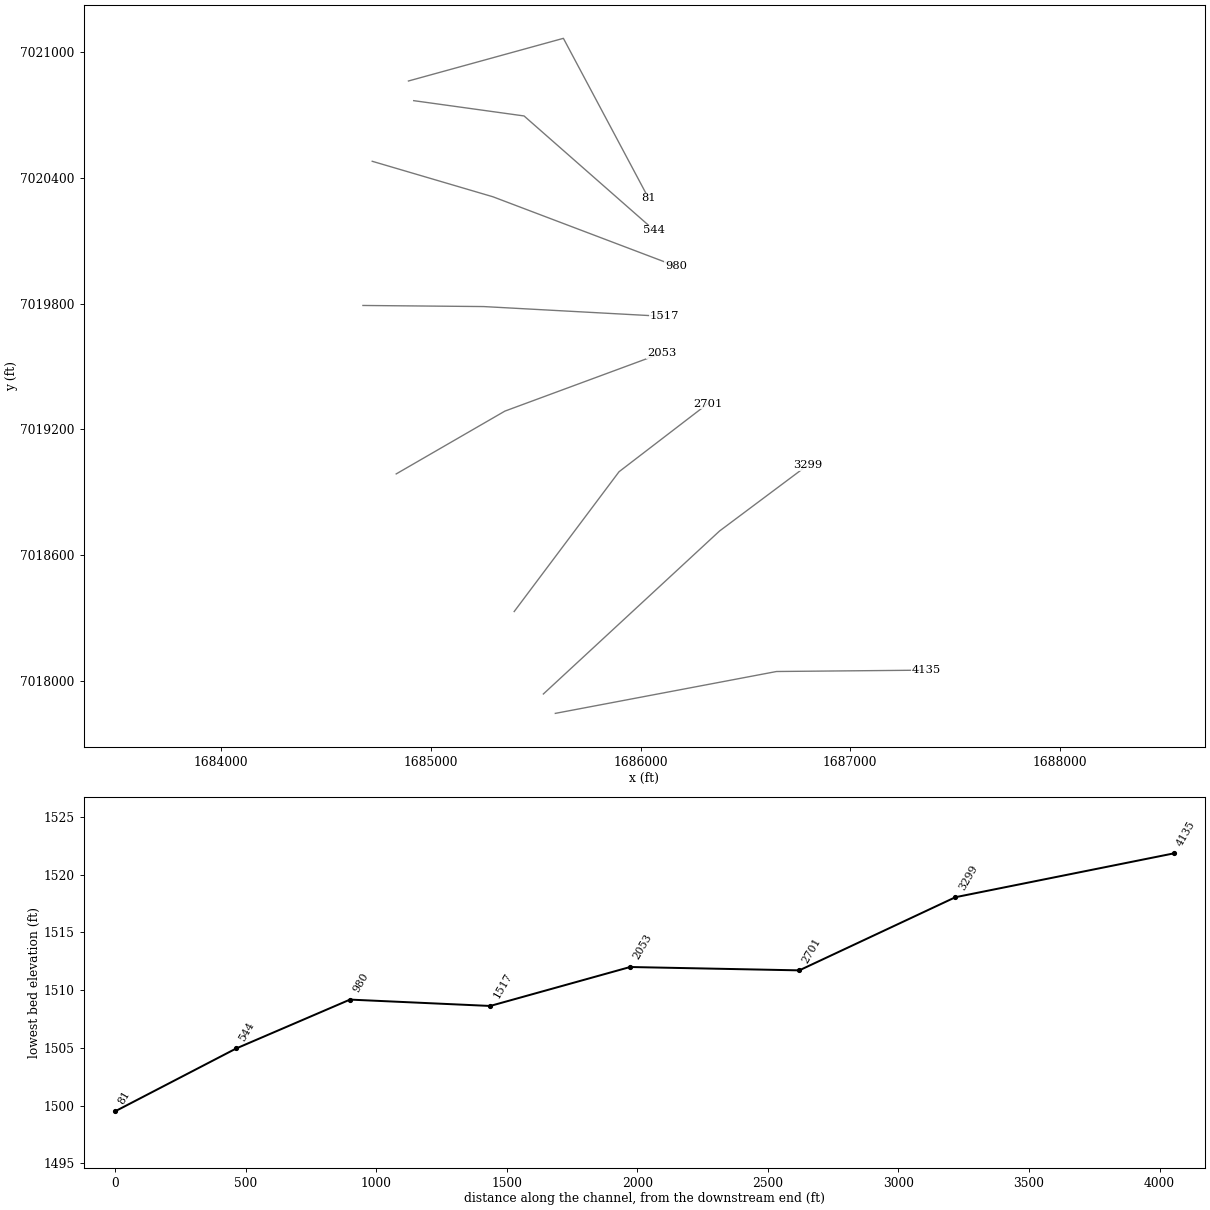
HEC-RAS study Chimney Creek 1178.prj: Chimney Creek 1178 Base Level Engineering

--- Chimney Creek 1178.g01 (geometry) --- (continued)

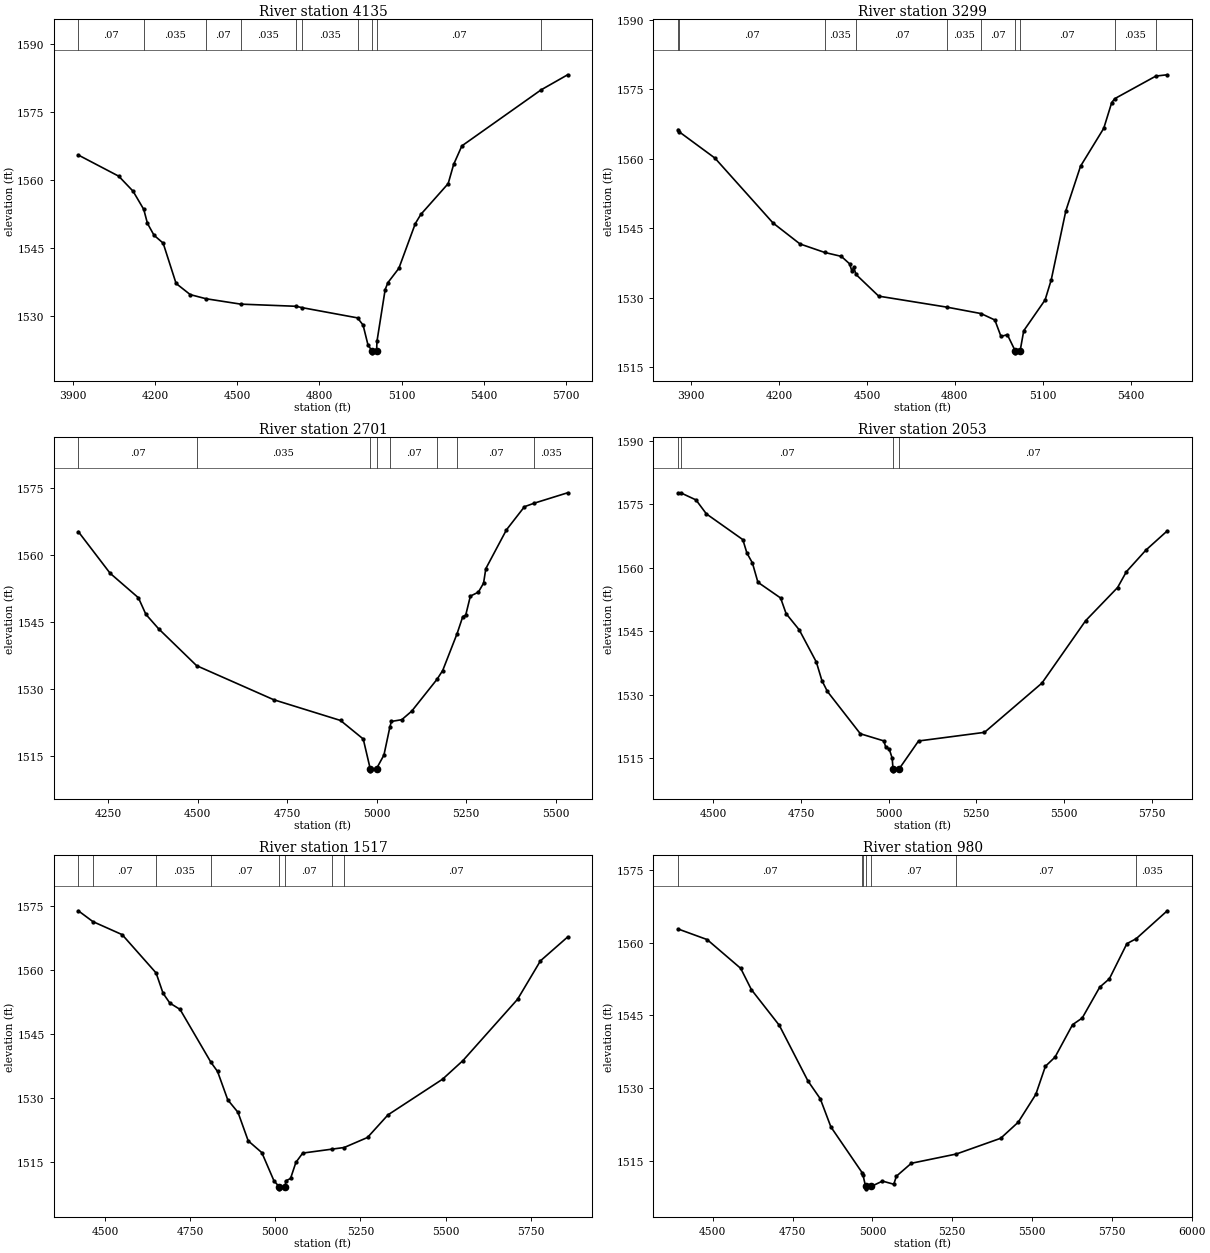
Type RM Length L Ch R = 1,4135,836,836,836
BEGIN DESCRIPTION:
Mapping XS d4734c4a
END DESCRIPTION:
XS GIS Cut Line= 3
      1685593.51      7017845.82      1686648.18      7018045.47
      1687361.05      7018051.97
#Sta/Elev= 30
  3919.8 1565.56  4067.4 1560.88  4119.7 1557.56  4158.7 1553.54  4172.1 1550.46
  4196.1 1547.83  4229.5 1546.08  4276.7 1537.17  4328.4 1534.70  4386.0 1533.79
  4512.3 1532.60  4714.9 1532.12  4736.0 1531.83  4939.0 1529.56  4959.4 1527.96
  4977.3 1523.57  4991.2 1522.33  4991.7 1521.83  5008.8 1522.33  5010.0 1524.35
  5040.0 1535.83  5050.0 1537.35  5090.0 1540.52  5150.0 1550.40  5170.0 1552.42
  5270.0 1559.24  5290.0 1563.49  5320.0 1567.58  5609.1 1579.96  5706.1 1583.30
#Mann=10,-1,0
  3919.8    0.07       0  4158.7   0.035       0  4386.0    0.07       0
  4512.3   0.035       0  4714.9    0.07       0  4736.0   0.035       0
  4939.0    0.07       0  4991.2    0.07       0  5008.8    0.07       0
  5609.1   0.035       0
Bank Sta=4991.2,5008.8
Exp/Cntr=0.3,0.1

Type RM Length L Ch R = 1,3299,598,598,598
BEGIN DESCRIPTION:
Mapping XS e4b588e1
END DESCRIPTION:
XS GIS Cut Line= 3
      1685536.50      7017938.28      1686376.33      7018715.18
      1686797.36      7019029.87
#Sta/Elev= 30
  3855.0 1566.33  3860.3 1565.79  3981.1 1560.16  4179.5 1546.12  4271.4 1541.59
  4355.7 1539.75  4412.6 1538.90  4440.9 1537.28  4448.3 1535.75  4455.1 1536.53
  4462.6 1534.99  4540.1 1530.30  4772.9 1527.92  4889.4 1526.53  4936.4 1525.14
  4957.4 1521.58  4979.0 1521.98  5005.3 1518.54  5005.8 1518.04  5022.9 1518.54
  5035.0 1522.82  5107.9 1529.48  5128.8 1533.82  5178.8 1548.79  5228.8 1558.40
  5308.0 1566.59  5335.1 1572.14  5345.1 1572.99  5485.9 1577.89  5524.7 1578.17
#Mann=10,-1,0
  3855.0   0.035       0  3860.3    0.07       0  4355.7   0.035       0
  4462.6    0.07       0  4772.9   0.035       0  4889.4    0.07       0
  5005.3    0.07       0  5022.9    0.07       0  5345.1   0.035       0
  5485.9    0.07       0
Bank Sta=5005.3,5022.9
Exp/Cntr=0.3,0.1

Type RM Length L Ch R = 1,2701,648,648,648
BEGIN DESCRIPTION:
Mapping XS 5ebbbf08
END DESCRIPTION:
XS GIS Cut Line= 3
      1685397.33      7018331.38      1685897.31      7018998.02
      1686320.58      7019322.61
#Sta/Elev= 30
  4166.9 1565.33  4255.6 1556.01  4334.7 1550.51  4355.6 1546.79  4391.0 1543.57
  4497.4 1535.28  4712.7 1527.65  4899.3 1523.00  4962.7 1518.85  4982.1 1512.21
  4982.6 1511.71  4999.8 1512.21  5020.5 1515.24  5037.2 1521.56  5041.3 1522.78
  5070.4 1523.18  5098.1 1525.09  5168.7 1532.22  5184.6 1534.19  5224.9 1542.48
  5240.7 1546.28  5248.9 1546.60  5261.9 1550.87  5284.3 1551.77  5298.8 1553.78
  5305.1 1557.04  5362.7 1565.73  5413.0 1570.92  5440.7 1571.72  5533.6 1574.04
#Mann=8,-1,0
  4166.9    0.07       0  4497.4   0.035       0  4982.1   0.035       0
  4999.8   0.035       0  5037.2    0.07       0  5168.7   0.035       0
  5224.9    0.07       0  5440.7   0.035       0
Bank Sta=4982.1,4999.8
Exp/Cntr=0.3,0.1

Type RM Length L Ch R = 1,2053,536,536,536
BEGIN DESCRIPTION:
Mapping XS a20654b3
END DESCRIPTION:
XS GIS Cut Line= 3
      1684834.80      7018987.60      1685353.04      7019287.08
      1686100.07      7019562.99
#Sta/Elev= 30
  4399.5 1577.72  4407.2 1577.75  4451.0 1576.06  4480.6 1572.76  4584.5 1566.67
  4596.1 1563.51  4611.8 1561.16  4627.5 1556.59  4692.2 1552.87  4707.9 1549.17
  4745.3 1545.34  4794.1 1537.72  4809.9 1533.35  4825.6 1530.77  4919.5 1520.77
  4986.4 1519.08  4992.2 1517.54  5001.8 1517.18  5010.3 1514.98  5012.6 1512.50
  5013.1 1512.00  5030.4 1512.50  5085.4 1519.06  5273.4 1521.10  5437.2 1532.75
  5561.7 1547.50  5652.9 1555.35  5678.0 1559.09  5733.5 1564.19  5794.4 1568.74
#Mann=4,-1,0
  4399.5   0.035       0  4407.2    0.07       0  5012.6    0.07       0
  5030.4    0.07       0
Bank Sta=5012.6,5030.4
Exp/Cntr=0.3,0.1

Type RM Length L Ch R = 1,1517,537,537,537
BEGIN DESCRIPTION:
Mapping XS 8a930657
END DESCRIPTION:
XS GIS Cut Line= 3
      1684676.16      7019790.77      1685251.69      7019785.56
      1686111.87      7019738.78
#Sta/Elev= 30
  4421.5 1573.97  4464.2 1571.43  4550.3 1568.36  4649.9 1559.36  4670.3 1554.60
  4690.3 1552.28  4720.3 1550.79  4811.0 1538.36  4830.4 1536.21  4860.4 1529.54
  4890.4 1526.61  4920.4 1519.91  4960.4 1517.14  4996.2 1510.49  5011.5 1509.13
  5012.0 1508.63  5029.3 1509.13  5030.4 1510.48  5044.8 1511.07  5060.5 1514.85
  5080.5 1517.03  5167.5 1517.97  5202.2 1518.34  5270.8 1520.70  5330.9 1526.01
  5491.1 1534.39  5551.2 1538.78  5711.4 1553.17  5778.7 1562.21  5858.5 1567.81
#Mann=8,-1,0
  4421.5   0.035       0  4464.2    0.07       0  4649.9   0.035       0
  4811.0    0.07       0  5011.5    0.07       0  5029.3    0.07       0
  5167.5   0.035       0  5202.2    0.07       0
Bank Sta=5011.5,5029.3
Exp/Cntr=0.3,0.1

Type RM Length L Ch R = 1,980,436,436,436
BEGIN DESCRIPTION:
Mapping XS fdc8c0b3
END DESCRIPTION:
XS GIS Cut Line= 3
      1684720.44      7020478.27      1685295.96      7020309.00
      1686168.37      7019978.26
#Sta/Elev= 30
  4390.6 1562.88  4482.1 1560.68  4587.3 1554.73  4620.7 1550.34  4708.1 1542.97
  4797.9 1531.47  4836.5 1527.79  4869.8 1521.97  4968.4 1512.45  4970.6 1511.98
  4978.4 1509.68  4978.9 1509.18  4996.3 1509.68  5031.3 1510.78  5066.8 1510.13
  5075.0 1511.79  5121.7 1514.46  5263.1 1516.38  5401.8 1519.63  5456.7 1522.95
  5511.7 1528.69  5541.8 1534.50  5572.0 1536.40  5626.9 1543.10  5657.1 1544.47
  5712.0 1550.85  5742.2 1552.58  5797.1 1559.84  5826.2 1560.86  5923.5 1566.63
#Mann=7,-1,0
  4390.6    0.07       0  4968.4   0.035       0  4970.6    0.07       0
  4978.4   0.035       0  4996.3    0.07       0  5263.1    0.07       0
  5826.2   0.035       0
Bank Sta=4978.4,4996.3
Exp/Cntr=0.3,0.1

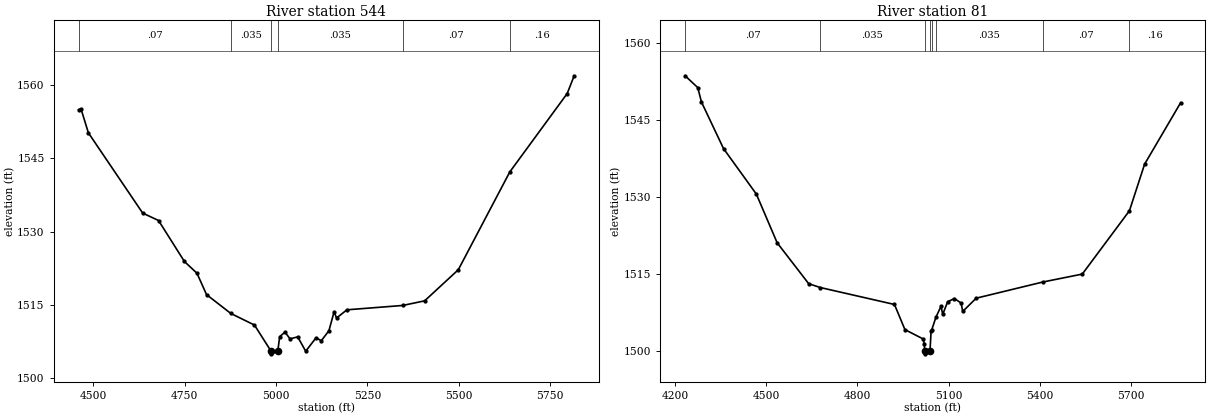
Type RM Length L Ch R = 1,544,463,463,463
BEGIN DESCRIPTION:
Mapping XS a1ae00bc
END DESCRIPTION:
XS GIS Cut Line= 3
      1684918.34      7020767.33      1685444.40      7020694.41
      1686064.16      7020150.17
#Sta/Elev= 30
  4460.1 1554.97  4466.8 1555.08  4486.8 1550.22  4635.4 1533.78  4678.8 1532.26
  4749.5 1523.87  4783.9 1521.46  4810.1 1517.08  4876.6 1513.22  4941.3 1510.84
  4987.0 1505.45  4987.5 1504.95  5004.9 1505.45  5010.2 1508.45  5024.5 1509.40
  5038.7 1508.02  5059.6 1508.43  5081.4 1505.48  5109.8 1508.25  5124.1 1507.63
  5145.0 1509.70  5159.2 1513.59  5165.8 1512.29  5194.3 1513.97  5346.9 1514.86
  5406.9 1515.81  5498.9 1522.17  5640.0 1542.23  5796.9 1558.27  5816.0 1561.91
#Mann=6,-1,0
  4460.1    0.07       0  4876.6   0.035       0  4987.0   0.035       0
  5004.9   0.035       0  5346.9    0.07       0  5640.0    0.16       0
Bank Sta=4987,5004.9
Exp/Cntr=0.3,0.1

Type RM Length L Ch R = 1,81,0,0,0
BEGIN DESCRIPTION:
Chimney Creek 1178 1.0
END DESCRIPTION:
XS GIS Cut Line= 3
      1684893.17      7020861.08      1685631.98      7021064.49
      1686037.88      7020302.56
#Sta/Elev= 30
  4233.7 1553.70  4275.3 1551.40  4287.5 1548.59  4360.1 1539.51  4468.0 1530.65
  4536.4 1521.16  4640.1 1513.19  4678.3 1512.44  4922.2 1509.14  4956.6 1504.24
  5015.0 1502.47  5020.7 1501.53  5021.1 1500.02  5021.6 1499.52  5039.0 1500.02
  5042.7 1503.97  5045.0 1504.23  5058.5 1506.64  5075.3 1508.80  5080.9 1507.21
  5097.2 1509.67  5119.2 1510.30  5141.2 1509.42  5146.8 1507.78  5190.8 1510.36
  5409.8 1513.51  5539.9 1515.06  5694.9 1527.40  5744.8 1536.48  5863.3 1548.45
#Mann=8,-1,0
  4233.7    0.07       0  4678.3   0.035       0  5021.1   0.035       0
  5039.0   0.035       0  5045.0    0.07       0  5058.5   0.035       0
  5409.8    0.07       0  5694.9    0.16       0
Bank Sta=5021.1,5039
Exp/Cntr=0.3,0.1

Chan Stop Cuts=-1