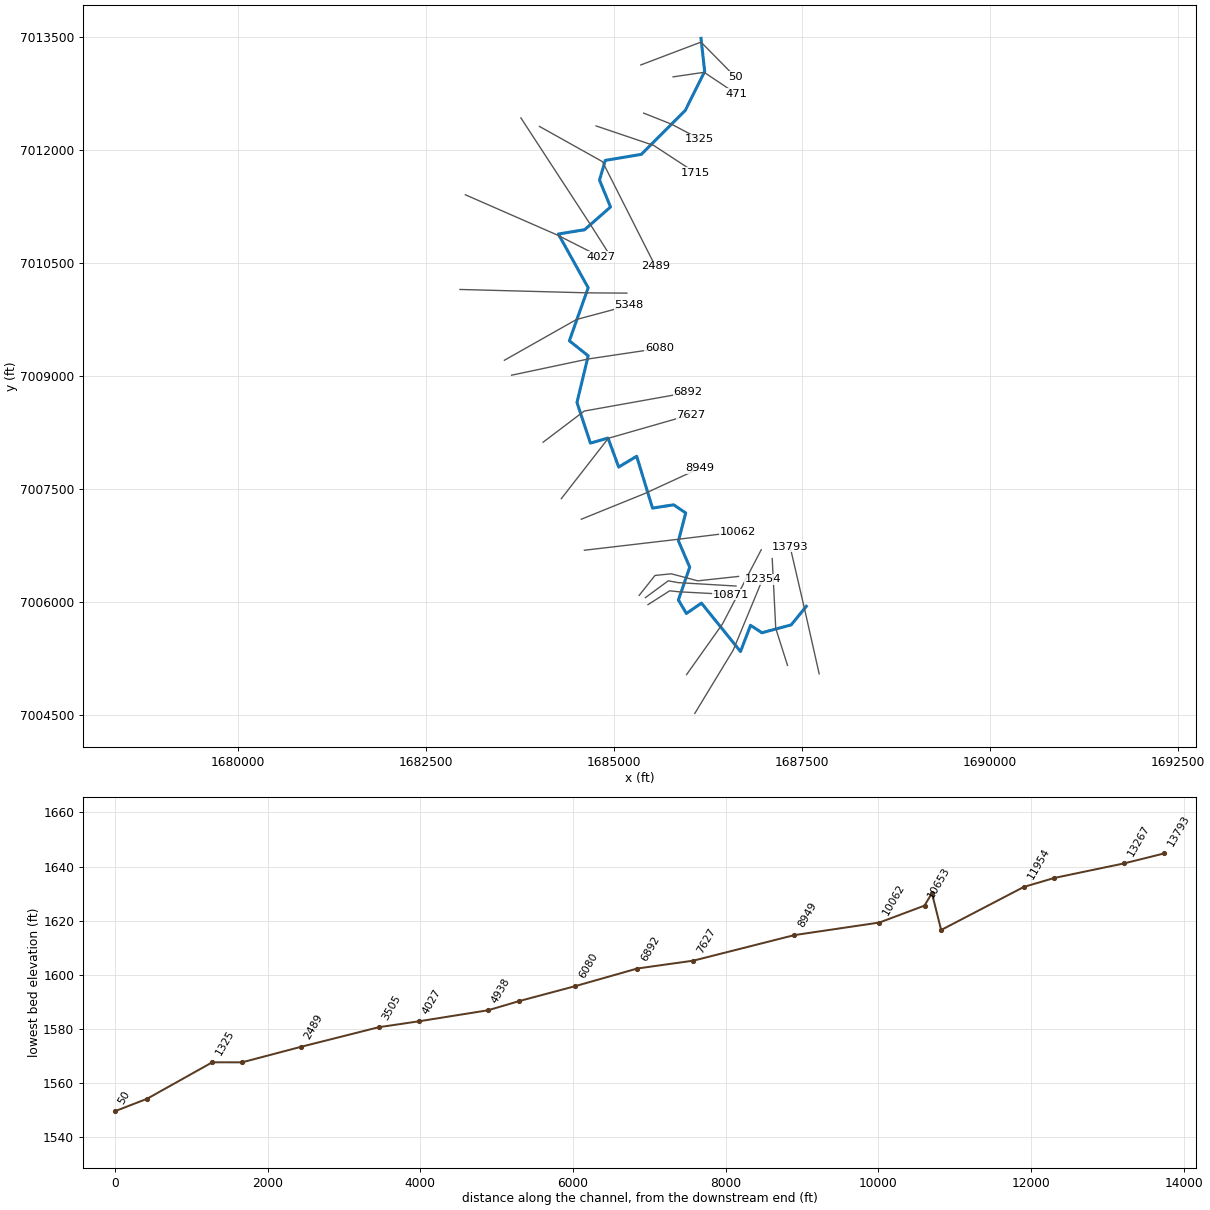
--- Chimney Creek 1179.prj (project) ---

Proj Title=Chimney Creek 1179 Base Level Engineering
Current Plan=p01
Default Exp/Contr=0.3,0.1
English Units
Geom File=g01
Flow File=f01
Plan File=p01
BEGIN DESCRIPTION:
Chimney Creek 1179
END DESCRIPTION:

--- Chimney Creek 1179.p01 (plan) ---

Plan Title=Multiple Run
Short Identifier=Multiple
Geom File=g01
Flow File=f01
Subcritical Flow
K Sum by GR= 0
Std Step Tol= 0.01
Critical Tol= 0.01
Num of Std Step Trials= 20
Max Error Tol= 0.3
Flow Tol Ratio= 0.001
Split Flow NTrial= 30
Split Flow Tol= 0.02
Split Flow Ratio= 0.02
Log Output Level= 0
Friction Slope Method= 1
Unsteady Friction Slope Method= 2
Unsteady Bridges Friction Slope Method= 1
Parabolic Critical Depth
Global Vel Dist=  1 , 1 , 1
Global Log Level= 0
CheckData=True
Encroach Param= -1, 0, 0, 0
BEGIN DESCRIPTION:
Multiple Run
END DESCRIPTION:

--- Chimney Creek 1179.f01 (steady flow) ---

Flow Title=Multiple
Number of Profiles=7
Profile Names=10-year,25-year,50-year,1pct_min,100-year,1pct_plu,500-year
River Rch & RM= Chimney Creek 11,Reach-1,13793
     267     371     457     281     560    1117     850
River Rch & RM= Chimney Creek 11,Reach-1,11954
     363     510     632     391     780    1556    1200
River Rch & RM= Chimney Creek 11,Reach-1,4027
     473     673     843     525    1048    2092    1640
River Rch & RM= Chimney Creek 11,Reach-1,1715
     547     784     987     618    1233    2459    1946
Boundary for River Rch & Prof#=Chimney Creek 11,Reach-1,1
Up Type=0
Dn Type=3
Dn Slope=0.005
Boundary for River Rch & Prof#=Chimney Creek 11,Reach-1,2
Up Type=0
Dn Type=3
Dn Slope=0.005
Boundary for River Rch & Prof#=Chimney Creek 11,Reach-1,3
Up Type=0
Dn Type=3
Dn Slope=0.005
Boundary for River Rch & Prof#=Chimney Creek 11,Reach-1,4
Up Type=0
Dn Type=3
Dn Slope=0.005
Boundary for River Rch & Prof#=Chimney Creek 11,Reach-1,5
Up Type=0
Dn Type=3
Dn Slope=0.005
Boundary for River Rch & Prof#=Chimney Creek 11,Reach-1,6
Up Type=0
Dn Type=3
Dn Slope=0.005
Boundary for River Rch & Prof#=Chimney Creek 11,Reach-1,7
Up Type=0
Dn Type=3
Dn Slope=0.005

--- Chimney Creek 1179.g01 (geometry) ---

Geom Title=Existing Conditions

River Reach=Chimney Creek 11,Reach-1
Reach XY= 30
      1687555.00      7005938.00      1687353.75      7005691.46
      1686964.75      7005587.09      1686813.51      7005685.43
      1686680.33      7005337.37      1686161.03      7005980.82
      1685960.47      7005843.10      1685854.51      7006022.80
      1686005.06      7006457.99      1685854.89      7006808.10
      1685951.93      7007179.70      1685790.96      7007287.90
      1685510.41      7007243.17      1685299.53      7007932.90
      1685060.47      7007789.59      1684918.66      7008174.81
      1684684.51      7008107.01      1684505.94      7008648.48
      1684655.14      7009267.75      1684404.88      7009467.89
      1684654.64      7010172.84      1684258.36      7010886.75
      1684607.29      7010943.81      1684952.02      7011246.34
      1684805.51      7011603.21      1684881.41      7011865.16
      1685361.12      7011945.89      1685947.14      7012531.83
      1686203.80      7013047.59      1686155.00      7013488.00

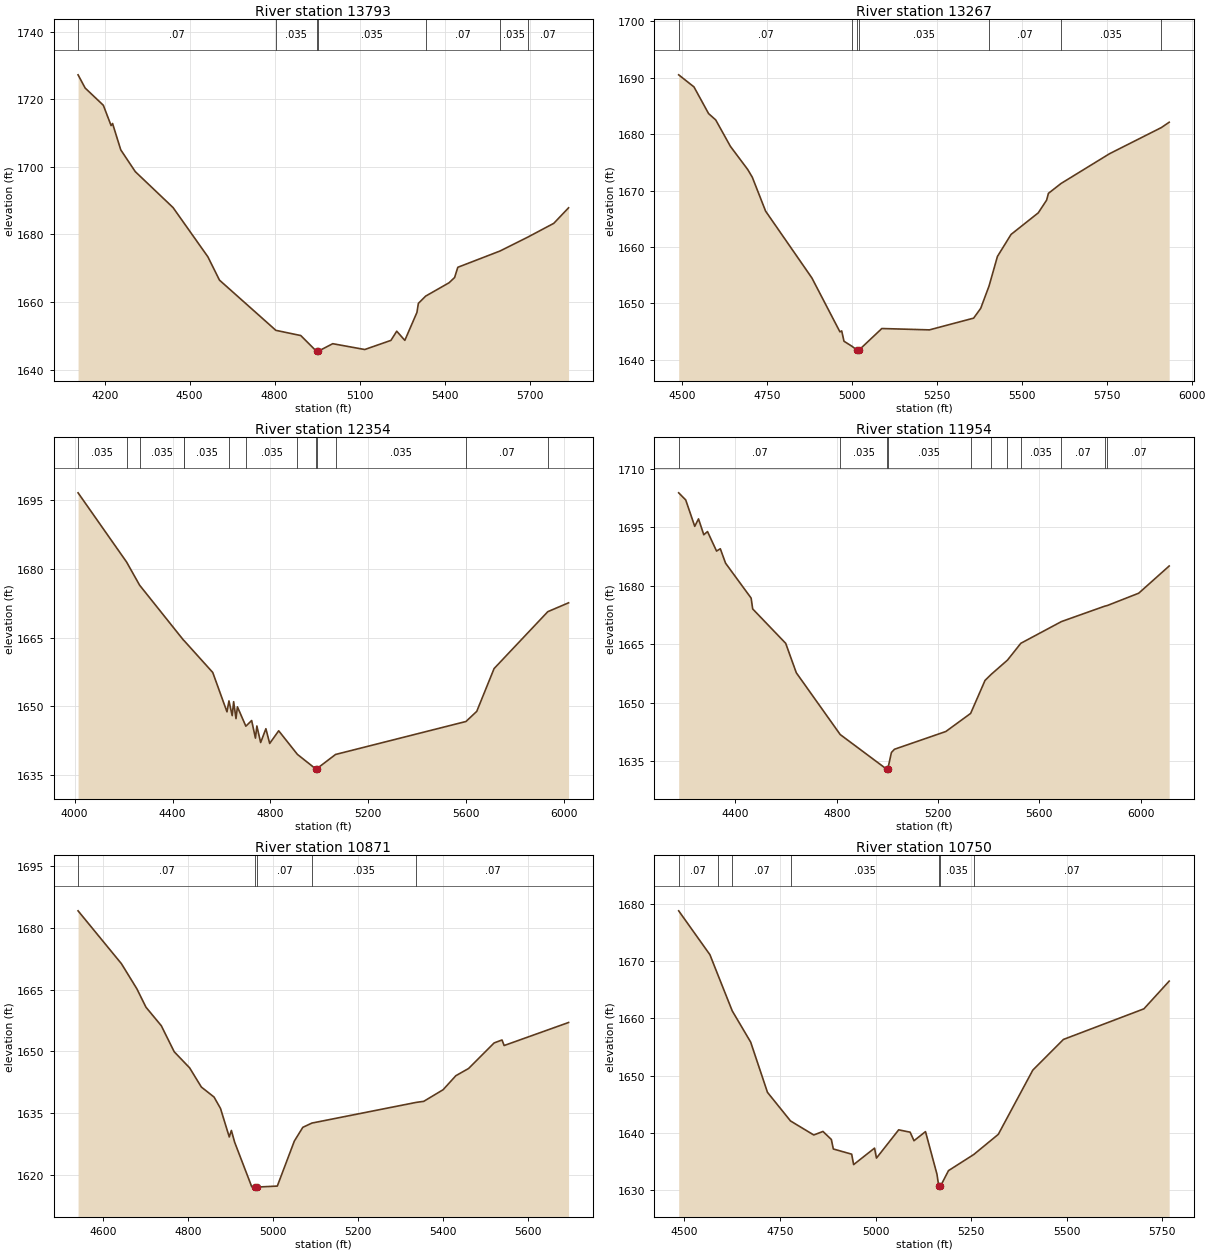
Type RM Length L Ch R = 1,13793,526,526,526
BEGIN DESCRIPTION:
Chimney Creek 1179 27.0
END DESCRIPTION:
XS GIS Cut Line= 3
      1687726.05      7005040.99      1687529.42      7005912.99
      1687339.88      7006728.87
#Sta/Elev= 30
  4106.1 1727.26  4131.1 1723.35  4195.3 1718.25  4222.7 1712.24  4227.9 1712.85
  4256.8 1705.06  4308.1 1698.60  4441.3 1687.98  4564.3 1673.40  4605.3 1666.49
  4804.3 1651.63  4892.4 1650.08  4948.3 1645.38  4948.6 1644.88  4952.3 1645.38
  5005.1 1647.67  5118.1 1645.95  5210.5 1648.65  5231.0 1651.37  5259.6 1648.66
  5302.3 1656.92  5307.4 1659.61  5333.2 1661.76  5415.8 1665.71  5435.3 1667.26
  5446.6 1670.29  5595.7 1675.11  5693.7 1679.22  5785.4 1683.30  5837.6 1687.90
#Mann=7,-1,0
  4106.1    0.07       0  4804.3   0.035       0  4948.3   0.035       0
  4952.3   0.035       0  5333.2    0.07       0  5595.7   0.035       0
  5693.7    0.07       0
Bank Sta=4948.3,4952.3
Exp/Cntr=0.3,0.1

Type RM Length L Ch R = 1,13267,913,913,913
BEGIN DESCRIPTION:
Mapping XS c325cd0c
END DESCRIPTION:
XS GIS Cut Line= 3
      1687304.86      7005154.04      1687148.62      7005646.19
      1687101.75      7006573.15
#Sta/Elev= 30
  4489.3 1690.50  4534.3 1688.36  4577.4 1683.63  4598.4 1682.51  4641.6 1677.83
  4692.8 1673.71  4706.1 1672.36  4745.3 1666.35  4881.6 1654.51  4964.2 1644.96
  4969.4 1645.13  4976.1 1643.30  4999.7 1642.40  5015.5 1641.69  5015.7 1641.19
  5019.5 1641.69  5087.6 1645.55  5227.7 1645.31  5357.9 1647.39  5378.7 1649.12
  5403.3 1653.08  5428.0 1658.32  5468.1 1662.22  5548.2 1666.04  5572.8 1668.29
  5578.2 1669.50  5615.4 1671.25  5758.4 1676.53  5910.6 1681.15  5933.8 1682.10
#Mann=7,-1,0
  4489.3    0.07       0  4999.7   0.035       0  5015.5   0.035       0
  5019.5   0.035       0  5403.3    0.07       0  5615.4   0.035       0
  5910.6    0.07       0
Bank Sta=5015.5,5019.5
Exp/Cntr=0.3,0.1

Type RM Length L Ch R = 1,12354,400,400,400
BEGIN DESCRIPTION:
Mapping XS fefa680a
END DESCRIPTION:
XS GIS Cut Line= 3
      1686072.84      7004515.27      1686583.26      7005356.43
      1686973.87      7006299.10
#Sta/Elev= 30
  4014.0 1696.64  4212.2 1681.52  4265.4 1676.46  4444.9 1664.44  4448.0 1664.29
  4564.3 1657.38  4622.5 1648.77  4630.6 1651.16  4643.8 1647.94  4649.7 1650.99
  4659.3 1647.28  4665.2 1649.86  4699.6 1645.63  4723.3 1646.87  4738.8 1643.02
  4744.6 1645.68  4760.1 1642.06  4781.5 1645.08  4797.0 1641.86  4833.8 1644.63
  4910.3 1639.47  4984.9 1636.31  4985.2 1635.81  4988.9 1636.31  5066.1 1639.45
  5599.1 1646.66  5643.1 1648.87  5714.0 1658.23  5933.4 1670.66  6018.3 1672.60
#Mann=13,-1,0
  4014.0   0.035       0  4212.2    0.07       0  4265.4   0.035       0
  4444.9    0.07       0  4448.0   0.035       0  4630.6    0.07       0
  4699.6   0.035       0  4910.3    0.07       0  4984.9    0.07       0
  4988.9    0.07       0  5066.1   0.035       0  5599.1    0.07       0
  5933.4   0.035       0
Bank Sta=4984.9,4988.9
Exp/Cntr=0.3,0.1

Type RM Length L Ch R = 1,11954,1083,1083,1083
BEGIN DESCRIPTION:
Mapping XS 9622be0a
END DESCRIPTION:
XS GIS Cut Line= 3
      1685963.48      7005030.92      1686440.03      7005702.78
      1686955.67      7006689.80
#Sta/Elev= 30
  4175.6 1703.77  4203.4 1701.95  4239.1 1695.18  4253.9 1697.10  4274.8 1693.03
  4289.5 1693.85  4325.2 1688.85  4340.0 1689.45  4360.9 1685.74  4461.8 1676.80
  4467.9 1674.04  4598.3 1665.22  4640.2 1657.68  4813.6 1641.86  4997.1 1632.99
  4997.4 1632.49  5001.4 1632.99  5015.8 1637.26  5027.8 1638.09  5230.8 1642.64
  5328.7 1647.27  5385.6 1655.73  5410.0 1657.28  5474.3 1660.93  5526.9 1665.23
  5687.5 1670.80  5857.9 1674.73  5869.1 1674.92  5992.5 1678.06  6112.9 1685.03
#Mann=11,-1,0
  4175.6    0.07       0  4813.6   0.035       0  4997.1   0.035       0
  5001.4   0.035       0  5328.7    0.07       0  5410.0   0.035       0
  5474.3    0.07       0  5526.9   0.035       0  5687.5    0.07       0
  5857.9   0.035       0  5869.1    0.07       0
Bank Sta=4997.1,5001.4
Exp/Cntr=0.3,0.1

Type RM Length L Ch R = 1,10871,121,121,121
BEGIN DESCRIPTION:
Mapping XS 1750590c
END DESCRIPTION:
XS GIS Cut Line= 4
      1685450.20      7005960.31      1685738.82      7006144.77
      1685856.01      7006131.75      1686550.20      7006094.87
#Sta/Elev= 30
  4540.6 1684.13  4642.8 1671.29  4679.2 1665.19  4700.6 1660.73  4736.7 1656.24
  4767.1 1649.92  4803.5 1646.00  4831.1 1641.35  4861.0 1638.92  4876.2 1636.15
  4896.8 1629.24  4901.8 1630.82  4909.5 1627.96  4949.7 1617.16  4957.6 1617.07
  4957.9 1616.57  4962.0 1617.07  5010.0 1617.31  5050.1 1628.23  5070.1 1631.57
  5091.3 1632.60  5337.9 1637.64  5355.0 1637.88  5400.6 1640.70  5430.6 1644.10
  5460.7 1645.86  5520.8 1652.06  5539.4 1652.78  5544.4 1651.43  5696.2 1657.02
#Mann=5,-1,0
  4540.6    0.07       0  4957.6    0.07       0  4962.0    0.07       0
  5091.3   0.035       0  5337.9    0.07       0
Bank Sta=4957.6,4962
Exp/Cntr=0.3,0.1

Type RM Length L Ch R = 1,10750,97,97,97
BEGIN DESCRIPTION:
Mapping XS b3619c36
END DESCRIPTION:
XS GIS Cut Line= 4
      1685415.49      7006053.64      1685719.29      7006277.15
      1685849.50      7006253.28      1686621.02      7006207.76
#Sta/Elev= 30
  4485.4 1678.78  4567.1 1671.12  4587.6 1667.66  4625.4 1661.32  4673.6 1655.87
  4717.5 1647.10  4777.8 1642.10  4838.6 1639.65  4862.6 1640.27  4884.6 1638.86
  4889.7 1637.21  4937.7 1636.30  4942.8 1634.48  4997.5 1637.36  5002.5 1635.62
  5060.6 1640.55  5090.6 1640.14  5100.6 1638.65  5130.7 1640.24  5160.7 1632.80
  5165.4 1630.70  5165.7 1630.20  5169.8 1630.70  5190.8 1633.43  5256.8 1636.24
  5321.0 1639.76  5411.2 1650.97  5491.3 1656.33  5701.7 1661.67  5767.8 1666.51
#Mann=7,-1,0
  4485.4    0.07       0  4587.6   0.035       0  4625.4    0.07       0
  4777.8   0.035       0  5165.4   0.035       0  5169.8   0.035       0
  5256.8    0.07       0
Bank Sta=5165.4,5169.8
Exp/Cntr=0.3,0.1

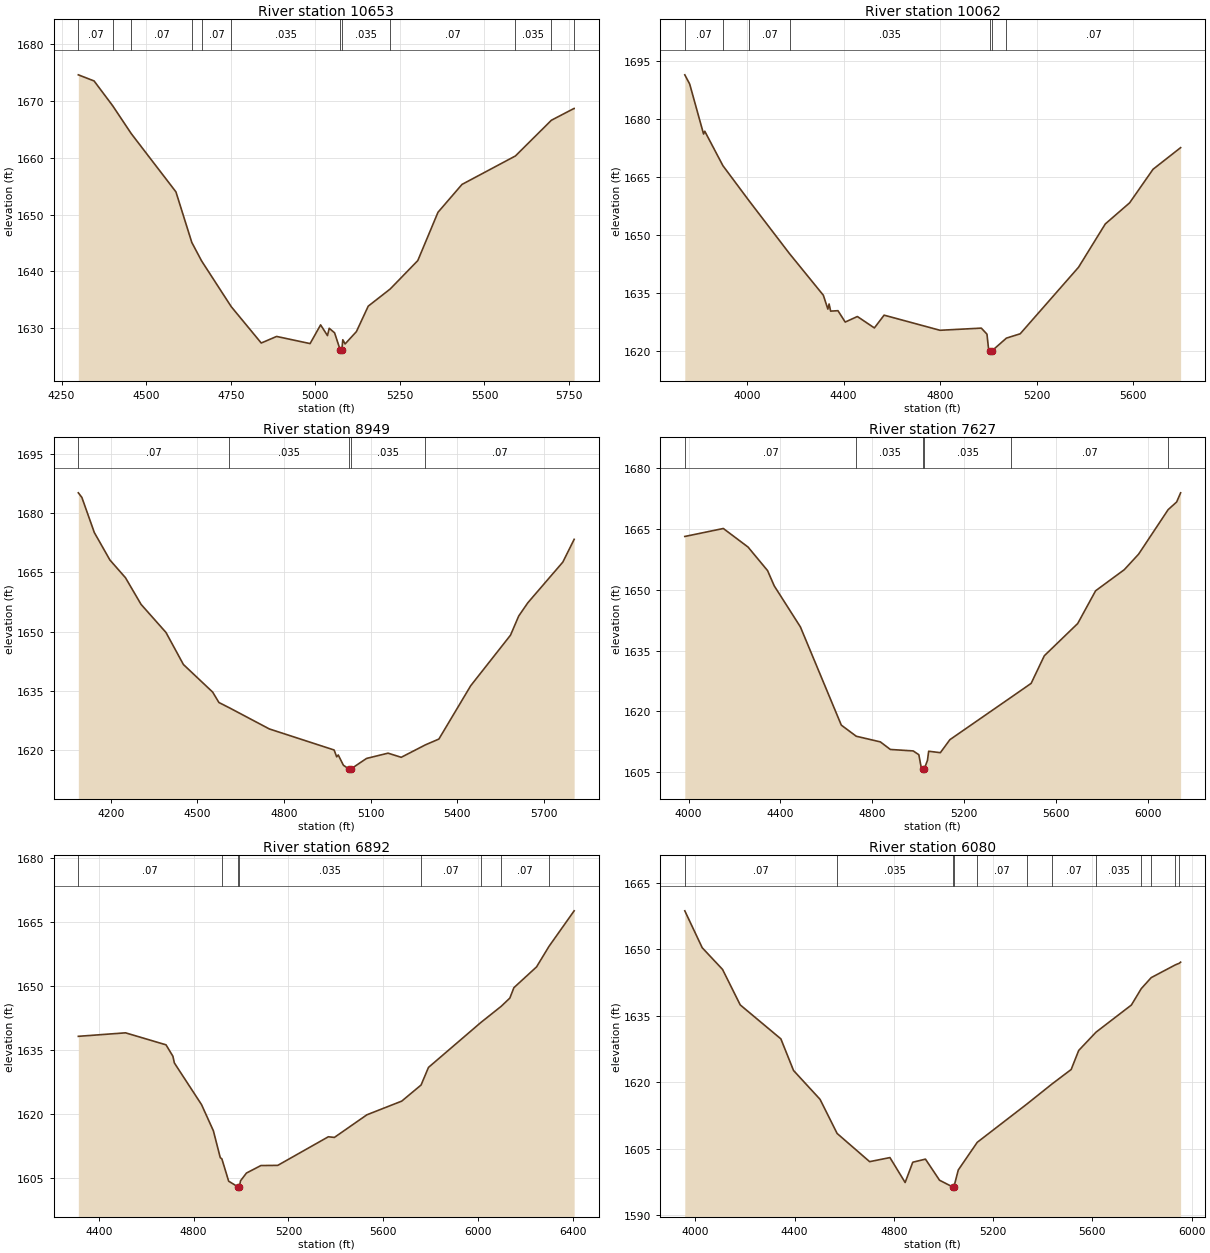
Type RM Length L Ch R = 1,10653,591,591,591
BEGIN DESCRIPTION:
Mapping XS 5e4f4bec
END DESCRIPTION:
XS GIS Cut Line= 6
      1685333.02      7006084.02      1685543.51      7006348.76
      1685760.52      7006370.46      1685899.41      7006333.57
      1686112.09      7006277.15      1686654.57      7006335.74
#Sta/Elev= 30
  4299.4 1674.62  4346.0 1673.54  4400.8 1669.18  4455.7 1664.27  4587.9 1654.00
  4634.8 1645.09  4663.8 1641.83  4751.5 1633.76  4840.1 1627.36  4885.5 1628.52
  4984.5 1627.26  5015.6 1630.56  5035.9 1628.67  5041.0 1629.96  5056.9 1629.16
  5073.9 1626.08  5074.2 1625.58  5078.3 1626.08  5081.2 1627.94  5088.0 1627.20
  5121.4 1629.37  5156.4 1633.86  5221.3 1636.88  5302.9 1641.89  5362.6 1650.40
  5433.6 1655.31  5591.4 1660.32  5697.9 1666.62  5764.6 1668.69  5765.1 1668.69
#Mann=12,-1,0
  4299.4    0.07       0  4400.8   0.035       0  4455.7    0.07       0
  4634.8   0.035       0  4663.8    0.07       0  4751.5   0.035       0
  5073.9   0.035       0  5078.3   0.035       0  5221.3    0.07       0
  5591.4   0.035       0  5697.9    0.07       0  5764.6   0.035       0
Bank Sta=5073.9,5078.3
Exp/Cntr=0.3,0.1

Type RM Length L Ch R = 1,10062,1113,1113,1113
BEGIN DESCRIPTION:
Mapping XS 62c5854e
END DESCRIPTION:
XS GIS Cut Line= 3
      1684604.83      7006683.72      1685848.34      7006829.12
      1686644.79      7006926.78
#Sta/Elev= 30
  3742.1 1691.45  3762.4 1689.06  3819.9 1676.11  3824.9 1676.83  3900.0 1667.91
  4008.5 1658.80  4176.5 1645.07  4316.2 1634.33  4334.9 1630.74  4340.0 1632.07
  4346.4 1630.21  4376.6 1630.33  4406.8 1627.38  4457.1 1628.82  4527.6 1625.86
  4567.9 1629.17  4799.4 1625.25  4970.6 1625.81  4994.1 1624.25  5000.8 1620.38
  5008.6 1619.83  5009.0 1619.33  5013.1 1619.83  5074.7 1623.22  5131.8 1624.34
  5373.6 1641.59  5484.4 1652.81  5585.1 1658.27  5682.1 1666.97  5796.5 1672.58
#Mann=7,-1,0
  3742.1    0.07       0  3900.0   0.035       0  4008.5    0.07       0
  4176.5   0.035       0  5008.6   0.035       0  5013.1   0.035       0
  5074.7    0.07       0
Bank Sta=5008.6,5013.1
Exp/Cntr=0.3,0.1

Type RM Length L Ch R = 1,8949,1322,1322,1322
BEGIN DESCRIPTION:
Mapping XS 18cbf172
END DESCRIPTION:
XS GIS Cut Line= 3
      1684563.58      7007096.03      1685405.63      7007436.76
      1686140.66      7007775.00
#Sta/Elev= 30
  4087.5 1685.17  4099.8 1684.00  4143.0 1675.10  4196.9 1668.16  4250.9 1663.66
  4304.8 1656.92  4391.1 1649.81  4451.5 1641.69  4552.9 1634.70  4574.5 1632.07
  4610.1 1630.75  4749.2 1625.37  4973.6 1620.04  4982.4 1618.31  4987.8 1618.79
  5005.7 1616.18  5025.8 1615.19  5026.2 1614.69  5030.7 1615.19  5085.7 1617.90
  5160.3 1619.24  5206.0 1618.19  5289.9 1621.35  5336.4 1622.81  5446.7 1636.32
  5584.5 1649.12  5613.0 1653.98  5644.7 1657.34  5765.7 1667.62  5805.0 1673.39
#Mann=5,-1,0
  4087.5    0.07       0  4610.1   0.035       0  5025.8   0.035       0
  5030.7   0.035       0  5289.9    0.07       0
Bank Sta=5025.8,5030.7
Exp/Cntr=0.3,0.1

Type RM Length L Ch R = 1,7627,735,735,735
BEGIN DESCRIPTION:
Mapping XS 94b14ae6
END DESCRIPTION:
XS GIS Cut Line= 3
      1684297.71      7007369.59      1684922.73      7008171.70
      1686020.81      7008486.55
#Sta/Elev= 30
  3983.5 1663.20  4151.3 1665.17  4258.9 1660.59  4344.0 1654.77  4372.9 1651.01
  4486.9 1640.87  4665.1 1616.61  4730.0 1613.87  4835.2 1612.47  4878.6 1610.60
  4978.2 1610.24  5002.7 1609.30  5013.1 1606.13  5021.0 1605.75  5021.4 1605.25
  5026.0 1605.75  5040.3 1607.91  5045.5 1610.16  5096.4 1609.81  5138.0 1613.02
  5406.2 1623.55  5491.7 1626.92  5549.1 1633.74  5694.5 1641.70  5772.5 1649.79
  5897.4 1655.00  5959.8 1658.84  6088.4 1669.83  6125.4 1671.72  6142.7 1673.98
#Mann=6,-1,0
  3983.5    0.07       0  4730.0   0.035       0  5021.0   0.035       0
  5026.0   0.035       0  5406.2    0.07       0  6088.4   0.035       0
Bank Sta=5021,5026
Exp/Cntr=0.3,0.1

Type RM Length L Ch R = 1,6892,812,812,812
BEGIN DESCRIPTION:
Mapping XS f705f425
END DESCRIPTION:
XS GIS Cut Line= 3
      1684055.57      7008119.63      1684602.42      7008533.68
      1685985.25      7008781.08
#Sta/Elev= 30
  4314.1 1638.17  4513.1 1638.99  4683.8 1636.18  4712.9 1633.50  4719.1 1631.92
  4833.6 1622.16  4883.5 1616.03  4912.6 1609.72  4919.3 1609.45  4948.0 1604.20
  4988.2 1602.84  4988.6 1602.34  4993.2 1602.84  4997.9 1604.28  5023.0 1606.11
  5083.9 1607.87  5155.0 1607.91  5368.4 1614.62  5393.7 1614.46  5530.9 1619.77
  5677.9 1622.98  5759.3 1626.75  5790.5 1630.88  6010.2 1641.36  6097.6 1645.23
  6133.6 1647.14  6150.6 1649.57  6246.2 1654.45  6298.4 1659.24  6404.8 1667.60
#Mann=8,-1,0
  4314.1    0.07       0  4919.3   0.035       0  4988.2   0.035       0
  4993.2   0.035       0  5759.3    0.07       0  6010.2   0.035       0
  6097.6    0.07       0  6298.4   0.035       0
Bank Sta=4988.2,4993.2
Exp/Cntr=0.3,0.1

Type RM Length L Ch R = 1,6080,732,732,732
BEGIN DESCRIPTION:
Mapping XS b6b8f084
END DESCRIPTION:
XS GIS Cut Line= 3
      1683636.31      7009010.25      1684657.11      7009226.39
      1685601.19      7009366.83
#Sta/Elev= 30
  3957.8 1658.73  4028.0 1650.39  4109.8 1645.49  4181.3 1637.46  4344.9 1629.79
  4396.0 1622.64  4502.7 1616.13  4571.6 1608.41  4702.6 1602.04  4784.4 1602.96
  4845.7 1597.33  4876.4 1601.91  4927.5 1602.61  4984.3 1597.84  5036.9 1596.33
  5037.3 1595.83  5042.1 1596.33  5059.8 1600.16  5136.2 1606.41  5335.6 1615.03
  5437.8 1619.61  5514.7 1622.87  5545.0 1627.17  5614.9 1631.31  5757.3 1637.44
  5797.2 1641.15  5837.1 1643.63  5934.9 1646.53  5949.9 1646.87  5955.7 1647.13
#Mann=12,-1,0
  3957.8    0.07       0  4571.6   0.035       0  5036.9   0.035       0
  5042.1   0.035       0  5136.2    0.07       0  5335.6   0.035       0
  5437.8    0.07       0  5614.9   0.035       0  5797.2    0.07       0
  5837.1   0.035       0  5934.9    0.07       0  5949.9   0.035       0
Bank Sta=5036.9,5042.1
Exp/Cntr=0.3,0.1

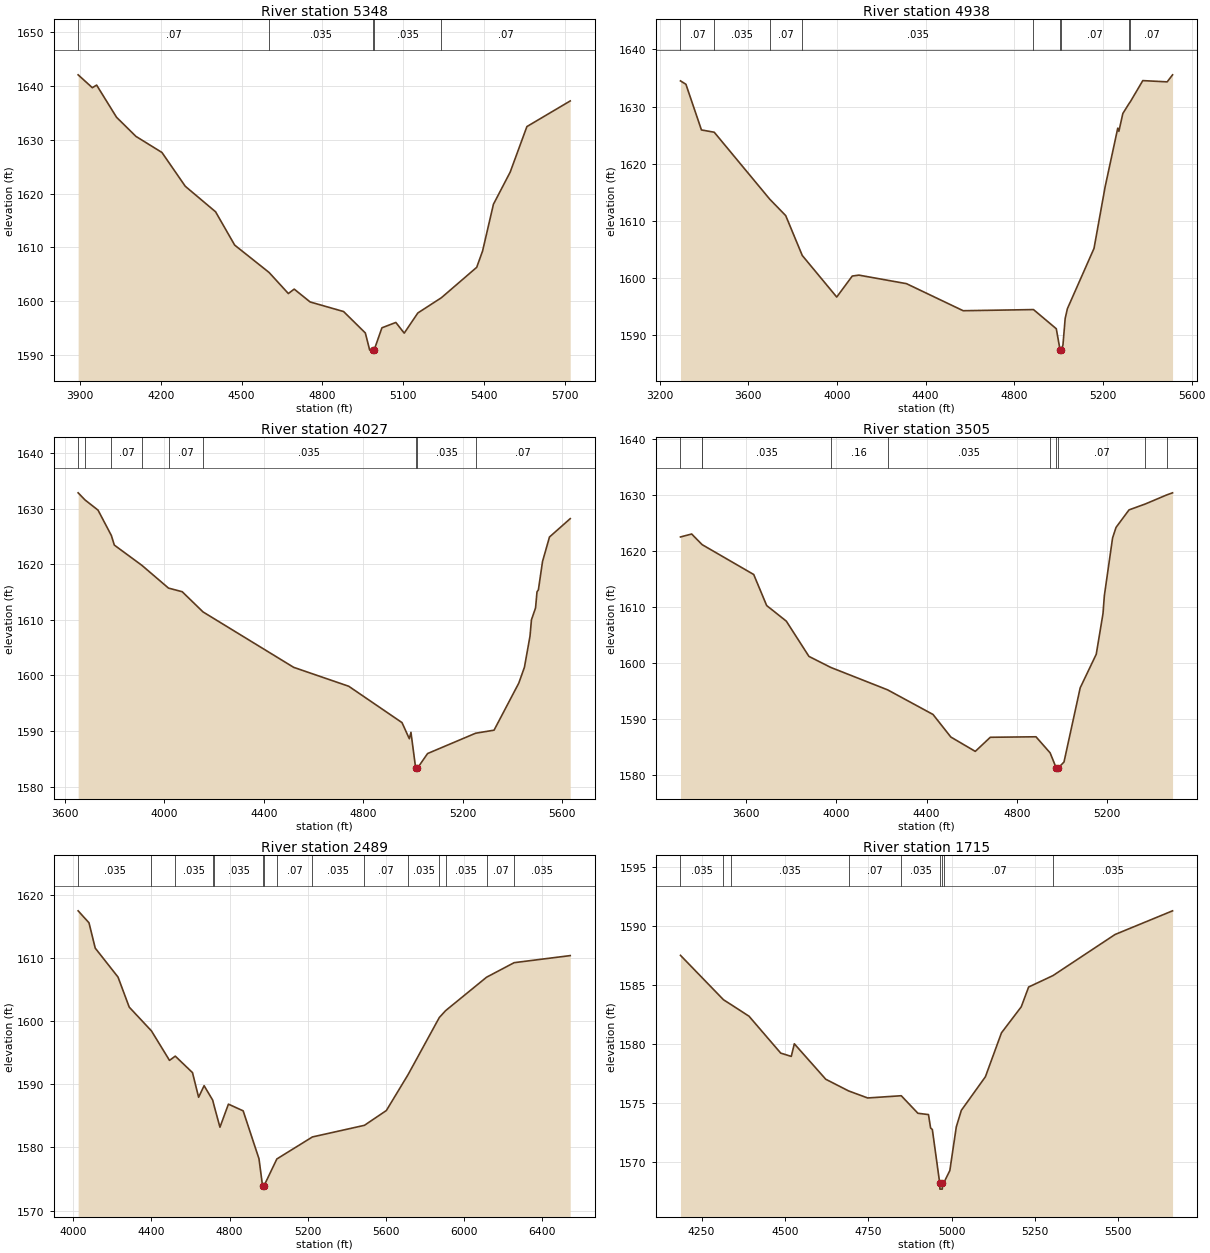
Type RM Length L Ch R = 1,5348,410,410,410
BEGIN DESCRIPTION:
Mapping XS 80267add
END DESCRIPTION:
XS GIS Cut Line= 3
      1683540.82      7009208.97      1684499.17      7009750.65
      1685200.31      7009938.08
#Sta/Elev= 30
  3893.1 1642.12  3945.8 1639.72  3961.7 1640.21  4035.7 1634.22  4107.5 1630.67
  4204.2 1627.67  4290.8 1621.38  4403.3 1616.63  4474.2 1610.43  4601.9 1605.34
  4673.4 1601.42  4695.1 1602.24  4754.3 1599.85  4878.4 1598.07  4959.2 1594.08
  4975.2 1590.91  4986.0 1590.83  4986.4 1590.33  4991.3 1590.83  5020.7 1595.04
  5072.4 1596.04  5103.5 1594.05  5154.0 1597.80  5241.5 1600.64  5372.6 1606.30
  5394.4 1609.34  5434.7 1618.04  5496.8 1624.01  5558.9 1632.49  5719.7 1637.26
#Mann=5,-1,0
  3893.1    0.07       0  4601.9   0.035       0  4986.0   0.035       0
  4991.3   0.035       0  5241.5    0.07       0
Bank Sta=4986,4991.3
Exp/Cntr=0.3,0.1

Type RM Length L Ch R = 1,4938,911,911,911
BEGIN DESCRIPTION:
Mapping XS 1e806449
END DESCRIPTION:
XS GIS Cut Line= 3
      1682950.55      7010149.96      1684655.42      7010104.82
      1685169.34      7010101.34
#Sta/Elev= 30
  3294.5 1634.48  3319.0 1633.89  3389.0 1625.91  3446.7 1625.51  3697.1 1613.81
  3769.1 1610.94  3843.8 1603.97  3999.2 1596.71  4069.2 1600.38  4099.2 1600.54
  4313.6 1599.05  4569.4 1594.32  4886.6 1594.52  4989.5 1591.17  5006.8 1587.41
  5007.3 1586.91  5012.2 1587.41  5019.5 1588.33  5029.5 1592.96  5039.5 1594.67
  5159.6 1605.21  5209.6 1615.95  5266.7 1626.22  5271.7 1625.67  5289.6 1628.78
  5317.6 1630.52  5324.1 1630.88  5379.6 1634.53  5489.6 1634.31  5513.9 1635.54
#Mann=9,-1,0
  3294.5    0.07       0  3446.7   0.035       0  3697.1    0.07       0
  3843.8   0.035       0  4886.6    0.07       0  5006.8    0.07       0
  5012.2    0.07       0  5317.6   0.035       0  5324.1    0.07       0
Bank Sta=5006.8,5012.2
Exp/Cntr=0.3,0.1

Type RM Length L Ch R = 1,4027,522,522,522
BEGIN DESCRIPTION:
Mapping XS 43e2700a
END DESCRIPTION:
XS GIS Cut Line= 3
      1683021.73      7011408.64      1684243.96      7010873.91
      1684819.40      7010582.73
#Sta/Elev= 30
  3653.8 1632.82  3681.5 1631.54  3733.8 1629.71  3787.4 1625.15  3799.3 1623.43
  3910.7 1619.77  4017.2 1615.70  4072.3 1615.05  4156.0 1611.42  4520.6 1601.46
  4742.1 1598.06  4956.3 1591.53  4985.7 1588.63  4992.3 1589.78  5011.3 1583.31
  5011.8 1582.81  5017.9 1583.31  5059.1 1585.97  5252.3 1589.62  5326.5 1590.17
  5426.1 1598.64  5448.6 1601.47  5471.0 1607.05  5476.9 1610.01  5493.4 1612.14
  5499.2 1615.02  5504.8 1615.39  5521.4 1620.48  5549.4 1624.88  5632.8 1628.18
#Mann=9,-1,0
  3653.8    0.07       0  3681.5   0.035       0  3787.4    0.07       0
  3910.7   0.035       0  4017.2    0.07       0  4156.0   0.035       0
  5011.3   0.035       0  5017.9   0.035       0  5252.3    0.07       0
Bank Sta=5011.3,5017.9
Exp/Cntr=0.3,0.1

Type RM Length L Ch R = 1,3505,1016,1016,1016
BEGIN DESCRIPTION:
Mapping XS 5e8eb2be
END DESCRIPTION:
XS GIS Cut Line= 3
      1683760.24      7012430.32      1684671.68      7011032.77
      1684945.12      7010603.09
#Sta/Elev= 30
  3311.1 1622.50  3360.6 1623.03  3404.8 1621.21  3407.2 1621.12  3635.2 1615.79
  3692.5 1610.24  3779.5 1607.45  3879.6 1601.15  3976.1 1599.18  4227.8 1595.17
  4428.7 1590.77  4507.7 1586.73  4615.8 1584.17  4682.2 1586.69  4884.4 1586.78
  4947.1 1583.90  4974.6 1581.14  4975.1 1580.64  4981.2 1581.14  5008.4 1582.27
  5080.1 1595.53  5151.2 1601.54  5181.1 1608.83  5187.0 1612.01  5223.4 1622.32
  5238.7 1624.21  5296.2 1627.34  5368.5 1628.40  5462.1 1630.00  5488.9 1630.39
#Mann=10,-1,0
  3311.1   0.035       0  3404.8    0.07       0  3407.2   0.035       0
  3976.1    0.16       0  4227.8   0.035       0  4947.1    0.07       0
  4974.6    0.07       0  4981.2    0.07       0  5368.5   0.035       0
  5462.1    0.07       0
Bank Sta=4974.6,4981.2
Exp/Cntr=0.3,0.1

Type RM Length L Ch R = 1,2489,774,774,774
BEGIN DESCRIPTION:
Mapping XS 763f83dc
END DESCRIPTION:
XS GIS Cut Line= 3
      1684006.74      7012317.40      1684845.24      7011848.67
      1685548.36      7010458.04
#Sta/Elev= 30
  4024.7 1617.42  4080.2 1615.53  4112.2 1611.52  4228.9 1606.94  4286.2 1602.19
  4400.0 1598.43  4492.4 1593.77  4521.9 1594.44  4610.1 1591.83  4641.4 1587.94
  4669.5 1589.77  4713.3 1587.49  4722.6 1586.38  4750.6 1583.20  4794.0 1586.85
  4869.4 1585.79  4950.5 1578.20  4968.7 1573.91  4969.2 1573.41  4975.7 1573.91
  5041.9 1578.18  5223.8 1581.66  5490.2 1583.50  5602.4 1585.84  5714.0 1591.54
  5873.5 1600.55  5905.9 1601.64  6115.3 1606.92  6256.4 1609.22  6543.6 1610.34
#Mann=15,-1,0
  4024.7   0.035       0  4400.0    0.16       0  4521.9   0.035       0
  4713.3    0.07       0  4722.6   0.035       0  4968.7   0.035       0
  4975.7   0.035       0  5041.9    0.07       0  5223.8   0.035       0
  5490.2    0.07       0  5714.0   0.035       0  5873.5    0.07       0
  5905.9   0.035       0  6115.3    0.07       0  6256.4   0.035       0
Bank Sta=4968.7,4975.7
Exp/Cntr=0.3,0.1

Type RM Length L Ch R = 1,1715,390,390,390
BEGIN DESCRIPTION:
Mapping XS d6f90b0e
END DESCRIPTION:
XS GIS Cut Line= 3
      1684760.08      7012323.58      1685525.74      7012064.89
      1686084.73      7011698.59
#Sta/Elev= 30
  4186.7 1587.51  4315.7 1583.74  4339.5 1583.31  4392.4 1582.34  4487.4 1579.21
  4519.1 1578.93  4528.3 1580.00  4622.6 1576.99  4691.0 1576.00  4748.4 1575.40
  4849.1 1575.59  4899.1 1574.10  4930.8 1573.99  4937.2 1572.85  4942.4 1572.72
  4964.6 1568.16  4965.1 1567.66  4972.2 1567.66  4972.7 1568.16  4977.5 1568.24
  4994.9 1569.24  5014.3 1572.95  5029.4 1574.35  5101.6 1577.20  5149.8 1580.93
  5209.2 1583.14  5231.3 1584.82  5304.3 1585.79  5490.6 1589.28  5663.2 1591.29
#Mann=9,-1,0
  4186.7   0.035       0  4315.7    0.16       0  4339.5   0.035       0
  4691.0    0.07       0  4849.1   0.035       0  4964.6    0.07       0
  4972.7   0.035       0  4977.5    0.07       0  5304.3   0.035       0
Bank Sta=4964.6,4972.7
Exp/Cntr=0.3,0.1

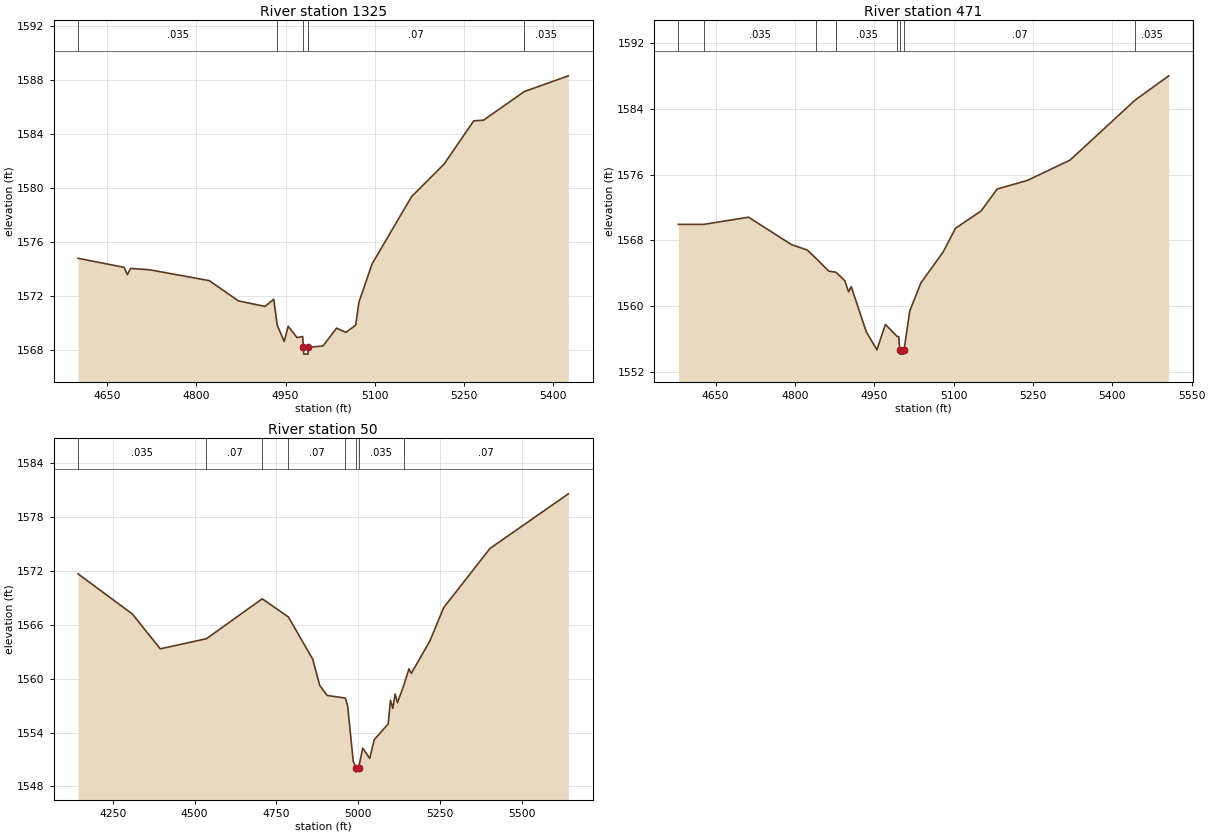
Type RM Length L Ch R = 1,1325,854,854,854
BEGIN DESCRIPTION:
Mapping XS 3f5996f9
END DESCRIPTION:
XS GIS Cut Line= 3
      1685393.11      7012493.60      1685759.89      7012348.19
      1686139.66      7012148.54
#Sta/Elev= 30
  4601.5 1574.78  4678.8 1574.11  4684.4 1573.57  4689.7 1574.03  4721.9 1573.93
  4822.1 1573.12  4870.8 1571.62  4915.5 1571.21  4930.2 1571.74  4936.1 1569.82
  4947.8 1568.61  4954.5 1569.74  4969.3 1568.90  4978.8 1568.97  4980.1 1568.17
  4980.6 1567.67  4987.8 1567.67  4988.3 1568.17  5013.1 1568.28  5035.7 1569.60
  5051.4 1569.28  5067.8 1569.82  5073.5 1571.55  5095.5 1574.37  5161.6 1579.35
  5216.5 1581.78  5266.2 1584.98  5282.6 1585.03  5351.0 1587.15  5425.1 1588.32
#Mann=5,-1,0
  4601.5   0.035       0  4936.1    0.07       0  4980.1    0.07       0
  4988.3    0.07       0  5351.0   0.035       0
Bank Sta=4980.1,4988.3
Exp/Cntr=0.3,0.1

Type RM Length L Ch R = 1,471,421,421,421
BEGIN DESCRIPTION:
Mapping XS 4602b12e
END DESCRIPTION:
XS GIS Cut Line= 3
      1685783.80      7012975.80      1686196.08      7013036.56
      1686620.15      7012753.13
#Sta/Elev= 30
  4579.8 1569.96  4628.0 1569.96  4712.4 1570.83  4793.3 1567.51  4823.6 1566.83
  4840.7 1565.78  4864.0 1564.28  4877.7 1564.14  4894.4 1563.11  4901.5 1561.76
  4906.5 1562.39  4934.8 1556.92  4955.0 1554.71  4971.1 1557.80  4993.4 1556.32
  4996.5 1556.31  4997.9 1554.69  4998.4 1554.19  5005.8 1554.19  5006.3 1554.69
  5017.1 1559.43  5038.1 1562.84  5080.2 1566.60  5103.5 1569.48  5152.3 1571.61
  5182.3 1574.25  5239.3 1575.30  5320.0 1577.76  5442.9 1585.05  5506.6 1588.01
#Mann=8,-1,0
  4579.8    0.07       0  4628.0   0.035       0  4840.7    0.07       0
  4877.7   0.035       0  4993.4    0.07       0  4997.9    0.07       0
  5006.3    0.07       0  5442.9   0.035       0
Bank Sta=4997.9,5006.3
Exp/Cntr=0.3,0.1

Type RM Length L Ch R = 1,50,0,0,0
BEGIN DESCRIPTION:
Chimney Creek 1179 1.0
END DESCRIPTION:
XS GIS Cut Line= 3
      1685354.05      7013134.21      1686154.89      7013437.95
      1686606.24      7012980.13
#Sta/Elev= 30
  4143.5 1571.67  4309.8 1567.19  4394.9 1563.32  4536.3 1564.45  4706.7 1568.89
  4786.8 1566.87  4861.1 1562.17  4882.5 1559.25  4905.3 1558.13  4961.1 1557.83
  4968.0 1556.96  4985.1 1550.79  4993.2 1550.09  4993.7 1549.59  5001.6 1550.09
  5014.1 1552.26  5035.4 1551.12  5049.5 1553.21  5092.0 1554.96  5099.0 1557.59
  5106.1 1556.68  5113.1 1558.30  5120.3 1557.33  5139.0 1559.18  5155.6 1561.09
  5162.7 1560.59  5219.3 1564.18  5261.7 1567.91  5403.1 1574.49  5642.9 1580.58
#Mann=8,-1,0
  4143.5   0.035       0  4536.3    0.07       0  4706.7   0.035       0
  4786.8    0.07       0  4961.1   0.035       0  4993.2   0.035       0
  5001.6   0.035       0  5139.0    0.07       0
Bank Sta=4993.2,5001.6
Exp/Cntr=0.3,0.1

Chan Stop Cuts=-1