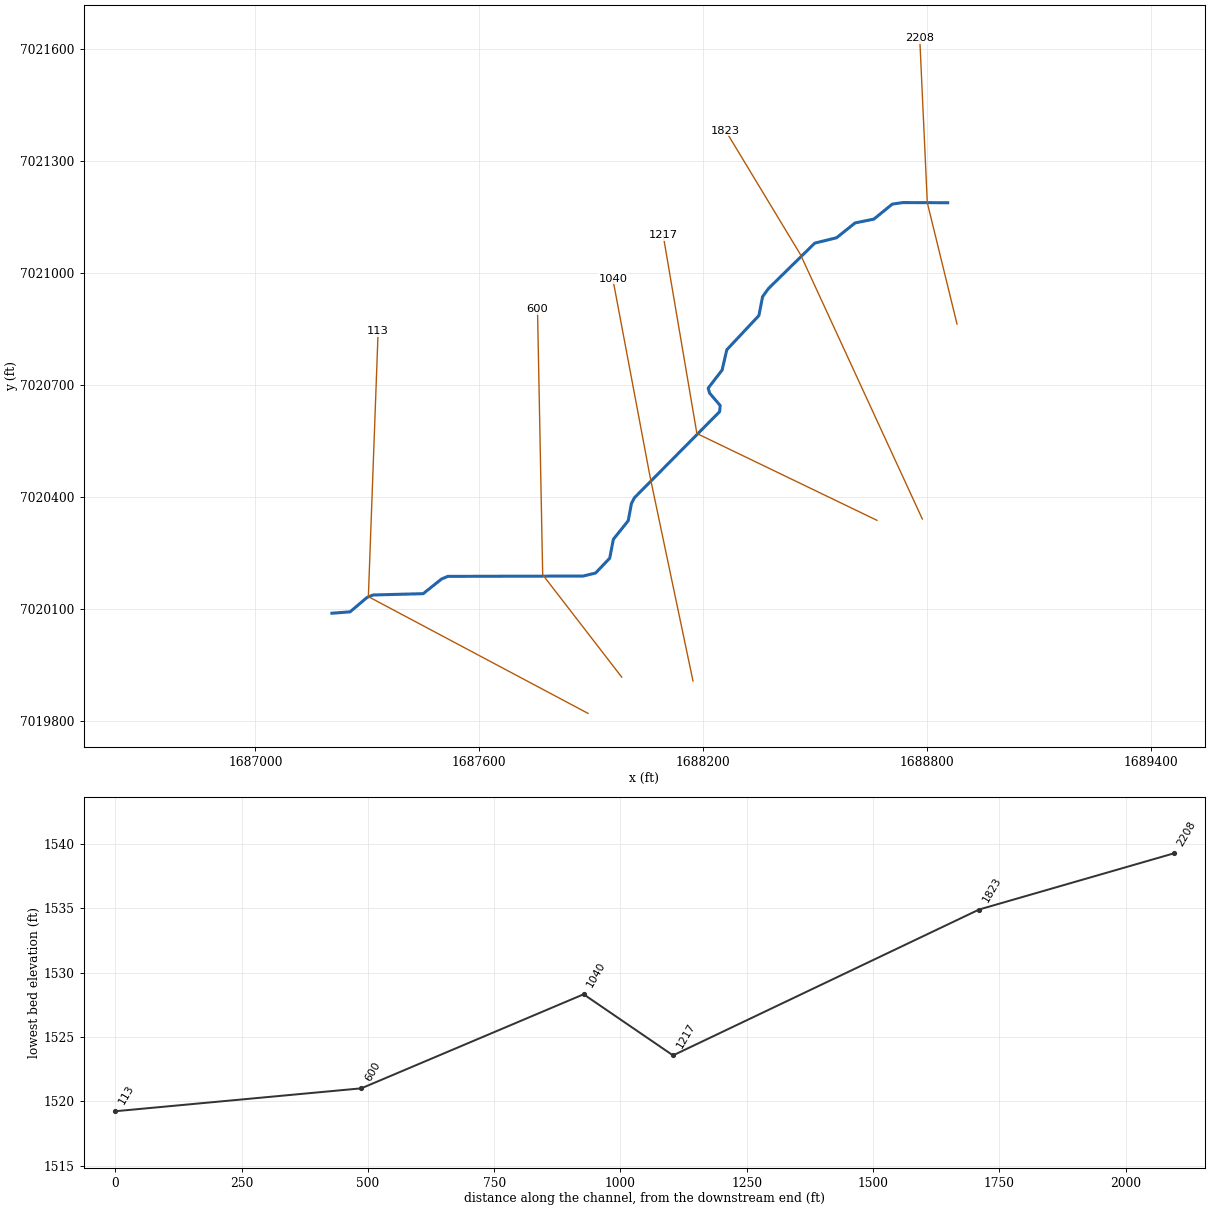
--- Chimney Creek 1181.prj (project) ---

Proj Title=Chimney Creek 1181 Base Level Engineering
Current Plan=p01
Default Exp/Contr=0.3,0.1
English Units
Geom File=g01
Flow File=f01
Plan File=p01
BEGIN DESCRIPTION:
Chimney Creek 1181
END DESCRIPTION:

--- Chimney Creek 1181.p01 (plan) ---

Plan Title=Multiple Run
Short Identifier=Multiple
Geom File=g01
Flow File=f01
Subcritical Flow
K Sum by GR= 0
Std Step Tol= 0.01
Critical Tol= 0.01
Num of Std Step Trials= 20
Max Error Tol= 0.3
Flow Tol Ratio= 0.001
Split Flow NTrial= 30
Split Flow Tol= 0.02
Split Flow Ratio= 0.02
Log Output Level= 0
Friction Slope Method= 1
Unsteady Friction Slope Method= 2
Unsteady Bridges Friction Slope Method= 1
Parabolic Critical Depth
Global Vel Dist=  1 , 1 , 1
Global Log Level= 0
CheckData=True
Encroach Param= -1, 0, 0, 0
BEGIN DESCRIPTION:
Multiple Run
END DESCRIPTION:

--- Chimney Creek 1181.f01 (steady flow) ---

Flow Title=Multiple
Number of Profiles=7
Profile Names=10-year,25-year,50-year,1pct_min,100-year,1pct_plu,500-year
River Rch & RM= Chimney Creek 11,Reach-1,2208
     285     397     492     304     606    1209     931
River Rch & RM= Chimney Creek 11,Reach-1,1217
     315     443     551     341     681    1359    1053
Boundary for River Rch & Prof#=Chimney Creek 11,Reach-1,1
Up Type=0
Dn Type=3
Dn Slope=0.005
Boundary for River Rch & Prof#=Chimney Creek 11,Reach-1,2
Up Type=0
Dn Type=3
Dn Slope=0.005
Boundary for River Rch & Prof#=Chimney Creek 11,Reach-1,3
Up Type=0
Dn Type=3
Dn Slope=0.005
Boundary for River Rch & Prof#=Chimney Creek 11,Reach-1,4
Up Type=0
Dn Type=3
Dn Slope=0.005
Boundary for River Rch & Prof#=Chimney Creek 11,Reach-1,5
Up Type=0
Dn Type=3
Dn Slope=0.005
Boundary for River Rch & Prof#=Chimney Creek 11,Reach-1,6
Up Type=0
Dn Type=3
Dn Slope=0.005
Boundary for River Rch & Prof#=Chimney Creek 11,Reach-1,7
Up Type=0
Dn Type=3
Dn Slope=0.005

--- Chimney Creek 1181.g01 (geometry) ---

Geom Title=Existing Conditions

River Reach=Chimney Creek 11,Reach-1
Reach XY= 30
      1688855.00      7021188.00      1688734.82      7021188.44
      1688706.54      7021184.28      1688657.18      7021144.12
      1688606.72      7021133.84      1688557.19      7021094.10
      1688498.94      7021079.86      1688374.79      7020958.09
      1688358.97      7020936.35      1688349.13      7020885.72
      1688263.14      7020794.04      1688250.56      7020739.65
      1688213.25      7020691.23      1688216.84      7020677.95
      1688245.40      7020644.66      1688243.76      7020628.00
      1688015.76      7020397.68      1688007.50      7020381.96
      1687998.90      7020335.81      1687959.20      7020286.23
      1687949.29      7020235.42      1687911.48      7020195.69
      1687877.96      7020187.60      1687515.50      7020186.78
      1687498.94      7020179.86      1687449.47      7020140.39
      1687315.47      7020136.87      1687298.84      7020130.10
      1687253.49      7020091.65      1687205.00      7020088.00

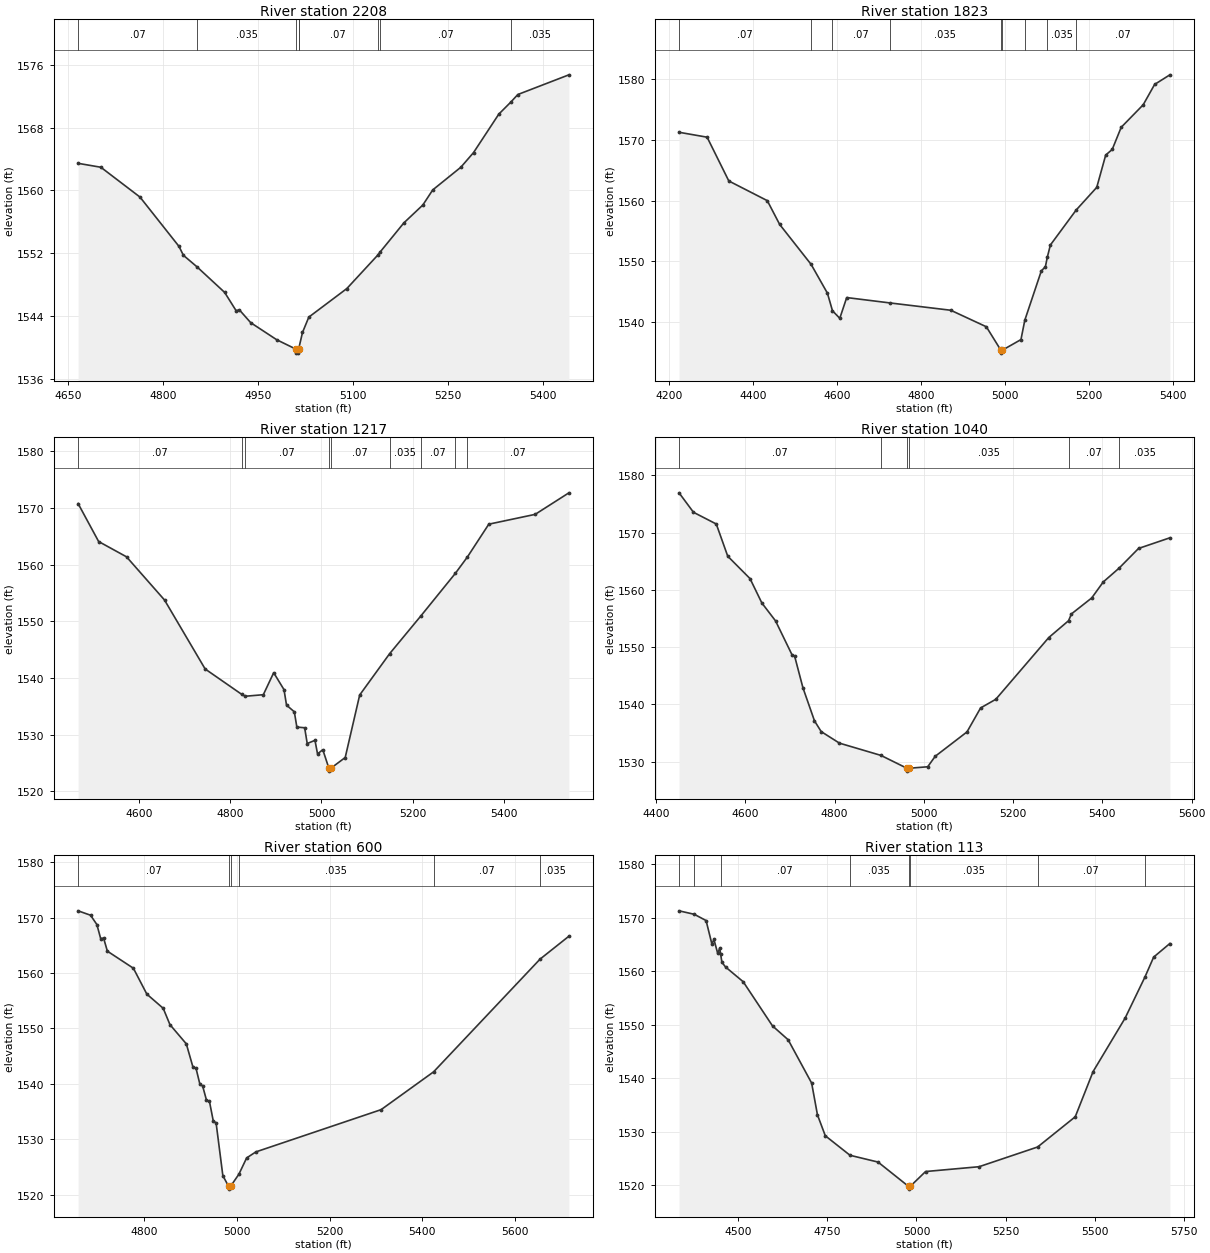
Type RM Length L Ch R = 1,2208,385,385,385
BEGIN DESCRIPTION:
Chimney Creek 1181 4.0
END DESCRIPTION:
XS GIS Cut Line= 3
      1688879.99      7020863.04      1688800.40      7021188.14
      1688780.14      7021628.57
#Sta/Elev= 30
  4665.3 1563.46  4701.3 1562.96  4763.1 1559.16  4824.8 1552.87  4831.7 1551.74
  4852.9 1550.29  4896.9 1547.01  4915.0 1544.68  4920.1 1544.79  4938.1 1543.15
  4979.3 1540.97  5009.8 1539.77  5010.0 1539.27  5013.5 1539.27  5013.8 1539.77
  5014.2 1539.91  5019.9 1541.90  5029.9 1543.86  5090.0 1547.50  5138.6 1551.74
  5142.6 1552.16  5180.1 1555.87  5210.1 1558.15  5225.7 1560.07  5270.1 1562.96
  5290.2 1564.83  5330.2 1569.74  5348.8 1571.24  5360.2 1572.23  5440.9 1574.74
#Mann=8,-1,0
  4665.3    0.07       0  4852.9   0.035       0  5009.8   0.035       0
  5013.8   0.035       0  5014.2    0.07       0  5138.6   0.035       0
  5142.6    0.07       0  5348.8   0.035       0
Bank Sta=5009.8,5013.8
Exp/Cntr=0.3,0.1

Type RM Length L Ch R = 1,1823,606,606,606
BEGIN DESCRIPTION:
Mapping XS b620c7c6
END DESCRIPTION:
XS GIS Cut Line= 3
      1688787.08      7020340.42      1688460.69      7021048.75
      1688259.64      7021381.52
#Sta/Elev= 30
  4223.6 1571.28  4290.4 1570.47  4342.1 1563.26  4433.7 1560.02  4463.2 1556.10
  4538.1 1549.52  4576.9 1544.78  4588.9 1541.89  4606.3 1540.64  4622.8 1544.06
  4725.3 1543.18  4870.6 1541.97  4955.3 1539.25  4989.7 1535.41  4989.9 1534.91
  4993.7 1535.41  5037.7 1537.14  5046.9 1540.34  5086.2 1548.45  5095.9 1549.14
  5100.4 1550.69  5107.8 1552.72  5169.1 1558.47  5218.2 1562.21  5239.5 1567.53
  5255.0 1568.45  5276.4 1572.10  5328.8 1575.81  5356.0 1579.16  5392.3 1580.74
#Mann=9,-1,0
  4223.6    0.07       0  4538.1   0.035       0  4588.9    0.07       0
  4725.3   0.035       0  4989.7   0.035       0  4993.7   0.035       0
  5046.9    0.07       0  5100.4   0.035       0  5169.1    0.07       0
Bank Sta=4989.7,4993.7
Exp/Cntr=0.3,0.1

Type RM Length L Ch R = 1,1217,177,177,177
BEGIN DESCRIPTION:
Mapping XS 505a4d85
END DESCRIPTION:
XS GIS Cut Line= 3
      1688665.56      7020336.94      1688182.91      7020569.59
      1688092.63      7021100.88
#Sta/Elev= 30
  4467.1 1570.77  4512.1 1564.07  4573.2 1561.37  4656.4 1553.75  4745.3 1541.59
  4825.8 1537.09  4833.5 1536.78  4872.7 1537.05  4895.4 1540.93  4918.0 1537.94
  4923.5 1535.21  4940.6 1534.03  4946.1 1531.34  4963.2 1531.22  4968.8 1528.44
  4985.8 1529.00  4991.4 1526.61  5002.9 1527.35  5016.3 1524.07  5016.6 1523.57
  5020.4 1524.07  5052.0 1525.97  5083.7 1537.00  5149.1 1544.27  5217.9 1550.97
  5293.2 1558.46  5319.7 1561.36  5366.4 1567.13  5467.9 1568.86  5541.8 1572.66
#Mann=9,-1,0
  4467.1    0.07       0  4825.8   0.035       0  4833.5    0.07       0
  5016.3    0.07       0  5020.4    0.07       0  5149.1   0.035       0
  5217.9    0.07       0  5293.2   0.035       0  5319.7    0.07       0
Bank Sta=5016.3,5020.4
Exp/Cntr=0.3,0.1

Type RM Length L Ch R = 1,1040,440,440,440
BEGIN DESCRIPTION:
Mapping XS 9f108f76
END DESCRIPTION:
XS GIS Cut Line= 3
      1688172.49      7019906.42      1688057.91      7020451.53
      1687957.52      7020984.64
#Sta/Elev= 30
  4451.7 1576.95  4484.0 1573.55  4535.1 1571.50  4560.8 1565.87  4610.7 1561.96
  4637.2 1557.70  4667.9 1554.57  4705.3 1548.56  4710.4 1548.47  4729.2 1542.89
  4755.1 1537.10  4770.1 1535.23  4811.0 1533.21  4903.9 1531.07  4962.2 1528.82
  4962.4 1528.32  4966.3 1528.82  5008.7 1529.08  5025.5 1530.91  5096.7 1535.17
  5127.2 1539.36  5161.2 1540.87  5279.9 1551.66  5324.2 1554.60  5330.7 1555.79
  5376.1 1558.58  5402.0 1561.38  5437.3 1563.78  5481.0 1567.23  5551.2 1569.09
#Mann=6,-1,0
  4451.7    0.07       0  4903.9   0.035       0  4962.2   0.035       0
  4966.3   0.035       0  5324.2    0.07       0  5437.3   0.035       0
Bank Sta=4962.2,4966.3
Exp/Cntr=0.3,0.1

Type RM Length L Ch R = 1,600,487,487,487
BEGIN DESCRIPTION:
Mapping XS 049cc071
END DESCRIPTION:
XS GIS Cut Line= 3
      1687981.53      7019916.80      1687769.72      7020191.12
      1687755.83      7020902.90
#Sta/Elev= 30
  4657.4 1571.22  4684.2 1570.43  4697.9 1568.75  4706.1 1566.22  4712.4 1566.30
  4720.6 1563.94  4776.7 1560.86  4805.7 1556.19  4841.0 1553.63  4855.5 1550.69
  4890.8 1547.22  4905.3 1542.98  4911.6 1542.85  4919.8 1540.04  4926.1 1539.59
  4934.3 1537.06  4940.6 1536.88  4948.8 1533.37  4955.1 1532.92  4969.6 1523.44
  4982.0 1521.51  4982.3 1521.01  4986.2 1521.51  5004.2 1523.70  5020.9 1526.64
  5040.9 1527.73  5310.9 1535.35  5424.1 1542.17  5653.6 1562.50  5715.9 1566.64
#Mann=6,-1,0
  4657.4    0.07       0  4982.0    0.07       0  4986.2    0.07       0
  5004.2   0.035       0  5424.1    0.07       0  5653.6   0.035       0
Bank Sta=4982,4986.2
Exp/Cntr=0.3,0.1

Type RM Length L Ch R = 1,113,0,0,0
BEGIN DESCRIPTION:
Chimney Creek 1181 1.0
END DESCRIPTION:
XS GIS Cut Line= 3
      1687891.21      7019819.61      1687302.58      7020132.46
      1687328.73      7020843.48
#Sta/Elev= 30
  4333.4 1571.27  4376.2 1570.62  4409.3 1569.45  4425.6 1565.06  4431.3 1565.91
  4441.9 1563.33  4447.6 1564.29  4449.9 1563.29  4453.7 1561.65  4463.9 1560.77
  4513.5 1558.01  4595.8 1549.75  4639.7 1547.16  4705.7 1539.06  4722.0 1533.12
  4744.0 1529.21  4813.4 1525.56  4892.1 1524.29  4978.0 1519.73  4978.2 1519.23
  4982.2 1519.73  5025.6 1522.52  5175.7 1523.42  5340.2 1527.11  5445.8 1532.76
  5495.9 1541.21  5585.9 1551.22  5641.4 1558.88  5666.0 1562.62  5711.5 1565.16
#Mann=8,-1,0
  4333.4    0.07       0  4376.2   0.035       0  4449.9    0.07       0
  4813.4   0.035       0  4978.0   0.035       0  4982.2   0.035       0
  5340.2    0.07       0  5641.4   0.035       0
Bank Sta=4978,4982.2
Exp/Cntr=0.3,0.1

Chan Stop Cuts=-1