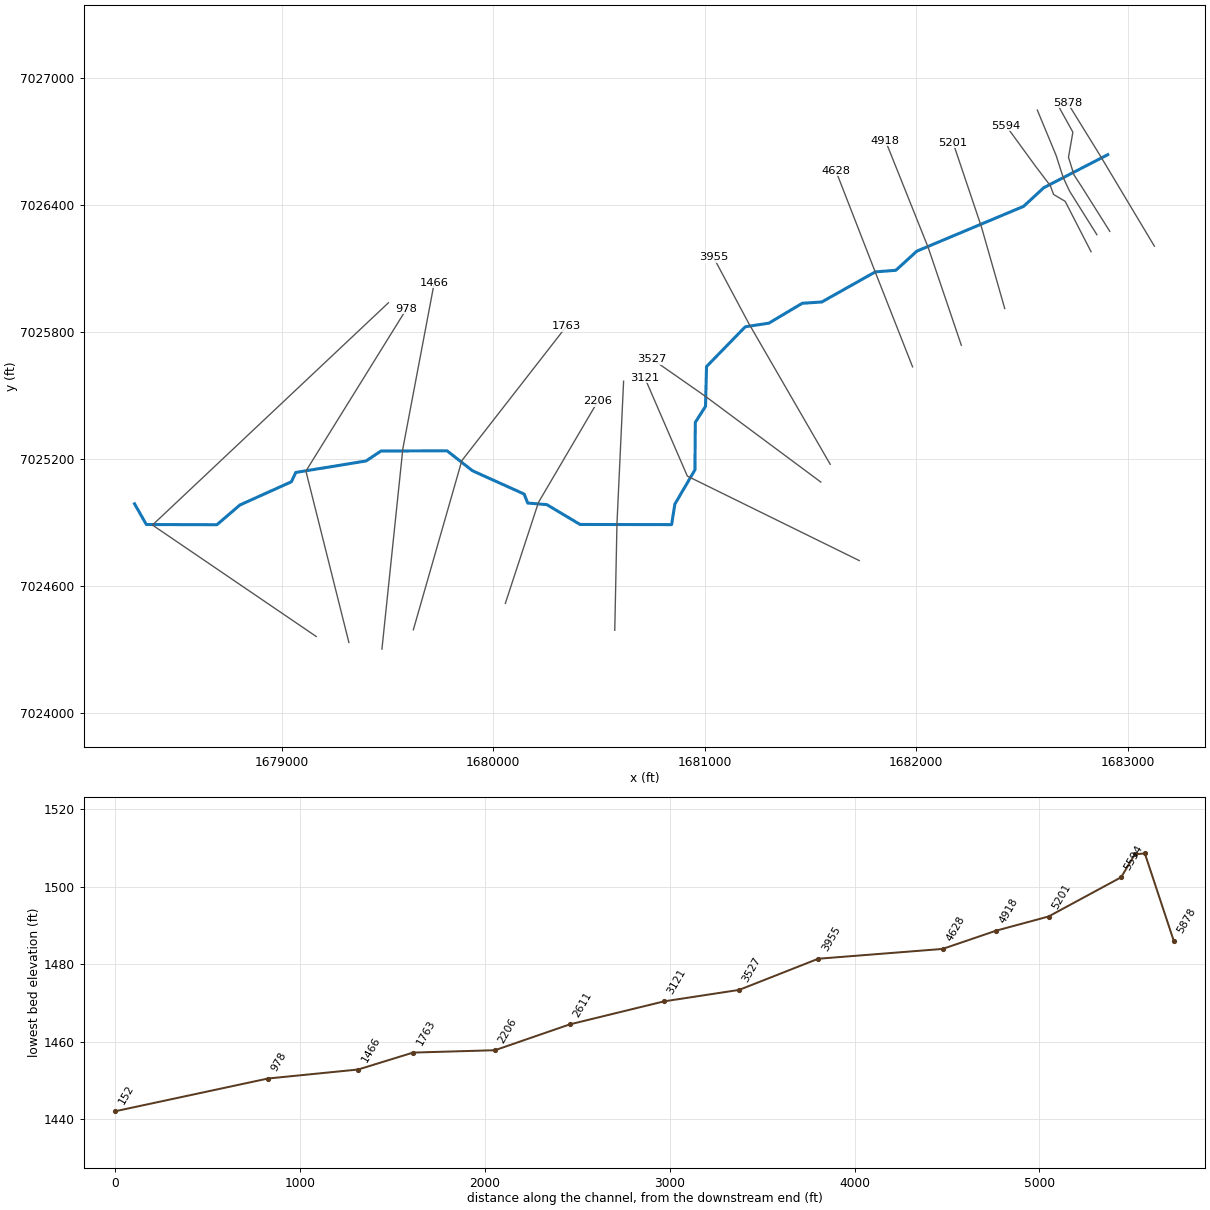
--- Chimney Creek 1182.prj (project) ---

Proj Title=Chimney Creek 1182 Base Level Engineering
Current Plan=p01
Default Exp/Contr=0.3,0.1
English Units
Geom File=g01
Flow File=f01
Plan File=p01
BEGIN DESCRIPTION:
Chimney Creek 1182
END DESCRIPTION:

--- Chimney Creek 1182.p01 (plan) ---

Plan Title=Multiple Run
Short Identifier=Multiple
Geom File=g01
Flow File=f01
Subcritical Flow
K Sum by GR= 0
Std Step Tol= 0.01
Critical Tol= 0.01
Num of Std Step Trials= 20
Max Error Tol= 0.3
Flow Tol Ratio= 0.001
Split Flow NTrial= 30
Split Flow Tol= 0.02
Split Flow Ratio= 0.02
Log Output Level= 0
Friction Slope Method= 1
Unsteady Friction Slope Method= 2
Unsteady Bridges Friction Slope Method= 1
Parabolic Critical Depth
Global Vel Dist=  1 , 1 , 1
Global Log Level= 0
CheckData=True
Encroach Param= -1, 0, 0, 0
BEGIN DESCRIPTION:
Multiple Run
END DESCRIPTION:

--- Chimney Creek 1182.f01 (steady flow) ---

Flow Title=Multiple
Number of Profiles=7
Profile Names=10-year,25-year,50-year,1pct_min,100-year,1pct_plu,500-year
River Rch & RM= Chimney Creek 11,Reach-1,5878
     407     579     725     452     903    1801    1417
Boundary for River Rch & Prof#=Chimney Creek 11,Reach-1,1
Up Type=0
Dn Type=3
Dn Slope=0.005
Boundary for River Rch & Prof#=Chimney Creek 11,Reach-1,2
Up Type=0
Dn Type=3
Dn Slope=0.005
Boundary for River Rch & Prof#=Chimney Creek 11,Reach-1,3
Up Type=0
Dn Type=3
Dn Slope=0.005
Boundary for River Rch & Prof#=Chimney Creek 11,Reach-1,4
Up Type=0
Dn Type=3
Dn Slope=0.005
Boundary for River Rch & Prof#=Chimney Creek 11,Reach-1,5
Up Type=0
Dn Type=3
Dn Slope=0.005
Boundary for River Rch & Prof#=Chimney Creek 11,Reach-1,6
Up Type=0
Dn Type=3
Dn Slope=0.005
Boundary for River Rch & Prof#=Chimney Creek 11,Reach-1,7
Up Type=0
Dn Type=3
Dn Slope=0.005

--- Chimney Creek 1182.g01 (geometry) ---

Geom Title=Existing Conditions

River Reach=Chimney Creek 11,Reach-1
Reach XY= 30
      1682905.00      7026638.00      1682602.71      7026482.15
      1682507.29      7026393.85      1682002.71      7026182.15
      1681903.50      7026091.62      1681806.59      7026084.17
      1681553.42      7025941.83      1681460.97      7025935.67
      1681303.41      7025841.83      1681191.70      7025824.60
      1681008.54      7025636.54      1681003.78      7025448.51
      1680955.52      7025372.78      1680953.80      7025148.50
      1680858.86      7024986.34      1680843.47      7024889.50
      1680410.93      7024890.24      1680253.35      7024984.15
      1680163.48      7024991.50      1680146.36      7025034.10
      1679902.71      7025143.85      1679782.35      7025238.19
      1679470.22      7025237.48      1679399.06      7025190.27
      1679066.95      7025136.07      1679046.35      7025091.91
      1678802.71      7024982.15      1678694.56      7024889.05
      1678360.69      7024889.93      1678305.00      7024988.00

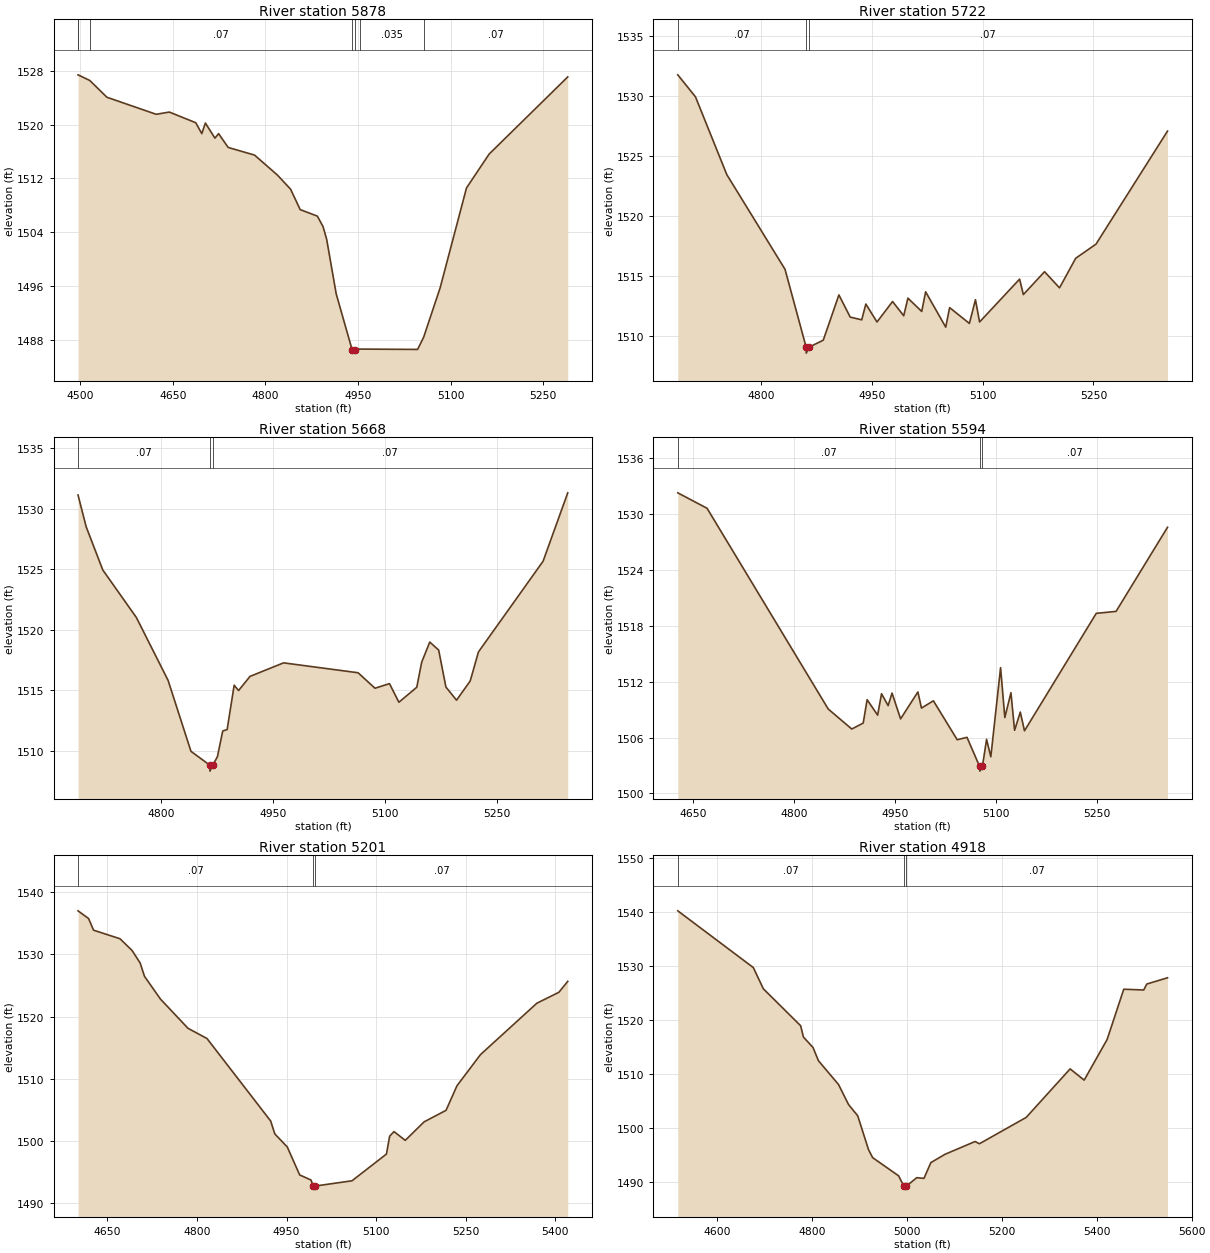
Type RM Length L Ch R = 1,5878,156,156,156
BEGIN DESCRIPTION:
Chimney Creek 1182 11.0
END DESCRIPTION:
XS GIS Cut Line= 3
      1683125.57      7026205.34      1682866.85      7026637.40
      1682714.76      7026883.97
#Sta/Elev= 30
  4496.4 1527.39  4496.5 1527.39  4515.6 1526.54  4543.2 1524.06  4623.0 1521.53
  4644.3 1521.86  4687.1 1520.28  4696.9 1518.66  4702.7 1520.23  4718.2 1517.99
  4724.1 1518.66  4739.6 1516.61  4782.4 1515.47  4819.4 1512.51  4840.7 1510.41
  4856.3 1507.38  4884.1 1506.41  4893.3 1504.86  4899.1 1503.01  4914.6 1494.88
  4940.4 1486.57  4940.7 1486.07  4944.4 1486.57  4952.7 1486.67  5046.5 1486.62
  5056.3 1488.44  5083.0 1495.77  5125.7 1510.60  5162.4 1515.63  5289.7 1527.08
#Mann=7,-1,0
  4496.4    0.07       0  4496.5   0.035       0  4515.6    0.07       0
  4940.4   0.035       0  4944.4    0.07       0  4952.7   0.035       0
  5056.3    0.07       0
Bank Sta=4940.4,4944.4
Exp/Cntr=0.3,0.1

Type RM Length L Ch R = 1,5722,54,54,54
BEGIN DESCRIPTION:
Mapping XS 61acd1ac
END DESCRIPTION:
XS GIS Cut Line= 6
      1682914.63      7026275.64      1682781.84      7026486.54
      1682745.38      7026542.53      1682719.34      7026625.87
      1682740.17      7026744.36      1682672.48      7026866.73
#Sta/Elev= 30
  4686.9 1531.77  4710.9 1529.93  4753.3 1523.44  4832.2 1515.53  4860.8 1509.03
  4861.0 1508.53  4864.8 1509.03  4884.0 1509.61  4905.2 1513.39  4920.5 1511.54
  4936.1 1511.31  4941.7 1512.63  4956.8 1511.13  4977.9 1512.84  4993.0 1511.65
  4998.7 1513.12  5017.4 1512.01  5022.7 1513.65  5049.9 1510.70  5055.2 1512.33
  5082.0 1511.01  5090.2 1512.99  5095.8 1511.13  5150.0 1514.71  5155.1 1513.42
  5183.8 1515.33  5204.1 1513.98  5226.0 1516.45  5253.5 1517.63  5350.4 1527.07
#Mann=3,-1,0
  4686.9    0.07       0  4860.8    0.07       0  4864.8    0.07       0
Bank Sta=4860.8,4864.8
Exp/Cntr=0.3,0.1

Type RM Length L Ch R = 1,5668,74,74,74
BEGIN DESCRIPTION:
Mapping XS 8b7342d1
END DESCRIPTION:
XS GIS Cut Line= 5
      1682853.46      7026259.98      1682724.55      7026465.71
      1682694.60      7026529.51      1682660.75      7026634.98
      1682572.20      7026848.53
#Sta/Elev= 30
  4689.4 1531.15  4700.3 1528.52  4722.5 1524.95  4767.5 1521.01  4809.9 1515.81
  4840.5 1509.94  4865.6 1508.80  4865.9 1508.30  4869.7 1508.80  4875.9 1509.49
  4883.0 1511.62  4888.9 1511.74  4898.3 1515.41  4904.2 1514.97  4919.5 1516.14
  4964.4 1517.26  5064.1 1516.44  5086.7 1515.16  5106.1 1515.54  5118.7 1514.00
  5142.6 1515.24  5149.2 1517.32  5160.0 1518.98  5171.9 1518.32  5181.6 1515.26
  5195.8 1514.17  5214.1 1515.76  5225.1 1518.16  5311.6 1525.67  5344.6 1531.33
#Mann=3,-1,0
  4689.4    0.07       0  4865.6    0.07       0  4869.7    0.07       0
Bank Sta=4865.6,4869.7
Exp/Cntr=0.3,0.1

Type RM Length L Ch R = 1,5594,393,393,393
BEGIN DESCRIPTION:
Mapping XS fadb7063
END DESCRIPTION:
XS GIS Cut Line= 6
      1682826.10      7026179.27      1682703.72      7026417.53
      1682649.03      7026450.09      1682633.40      7026491.75
      1682563.09      7026584.20      1682424.70      7026774.32
#Sta/Elev= 30
  4627.5 1532.27  4671.0 1530.61  4850.9 1509.06  4885.9 1506.91  4902.9 1507.55
  4908.7 1510.06  4924.3 1508.40  4930.1 1510.70  4939.9 1509.42  4945.7 1510.77
  4958.4 1508.00  4984.1 1510.89  4989.4 1509.16  5007.1 1509.94  5042.5 1505.76
  5057.0 1506.02  5075.8 1502.89  5076.1 1502.39  5079.9 1502.89  5086.1 1505.80
  5092.4 1503.93  5106.9 1513.50  5113.2 1508.14  5122.3 1510.81  5127.7 1506.77
  5136.2 1508.73  5142.4 1506.72  5249.0 1519.33  5278.4 1519.54  5354.8 1528.57
#Mann=3,-1,0
  4627.5    0.07       0  5075.8    0.07       0  5079.9    0.07       0
Bank Sta=5075.8,5079.9
Exp/Cntr=0.3,0.1

Type RM Length L Ch R = 1,5201,283,283,283
BEGIN DESCRIPTION:
Mapping XS da127c10
END DESCRIPTION:
XS GIS Cut Line= 3
      1682418.02      7025911.01      1682308.43      7026295.14
      1682174.11      7026693.76
#Sta/Elev= 30
  4600.8 1537.01  4618.5 1535.77  4626.8 1533.90  4671.1 1532.52  4691.3 1530.64
  4704.9 1528.61  4712.1 1526.48  4738.7 1522.84  4784.9 1518.13  4816.8 1516.48
  4923.4 1503.22  4930.4 1501.14  4951.2 1499.05  4972.0 1494.55  4991.1 1493.73
  4994.2 1492.77  4994.5 1492.27  4998.3 1492.77  5059.6 1493.61  5117.3 1497.91
  5122.6 1500.77  5129.9 1501.52  5148.8 1500.11  5180.3 1503.08  5217.1 1504.94
  5235.4 1508.89  5274.8 1513.90  5369.2 1522.16  5406.0 1523.91  5420.9 1525.67
#Mann=3,-1,0
  4600.8    0.07       0  4994.2    0.07       0  4998.3    0.07       0
Bank Sta=4994.2,4998.3
Exp/Cntr=0.3,0.1

Type RM Length L Ch R = 1,4918,290,290,290
BEGIN DESCRIPTION:
Mapping XS 37483f88
END DESCRIPTION:
XS GIS Cut Line= 3
      1682212.91      7025737.25      1682056.65      7026198.20
      1681854.14      7026704.48
#Sta/Elev= 30
  4517.1 1540.17  4676.3 1529.66  4697.4 1525.73  4776.0 1518.89  4781.9 1516.79
  4802.1 1514.86  4813.5 1512.41  4855.8 1508.01  4876.9 1504.30  4896.3 1502.21
  4919.1 1495.93  4927.8 1494.46  4982.5 1491.09  4993.8 1489.13  4994.1 1488.63
  4998.0 1489.13  5020.7 1490.75  5035.9 1490.62  5050.4 1493.54  5080.0 1495.07
  5143.6 1497.45  5152.7 1497.03  5251.3 1501.91  5343.9 1510.90  5373.5 1508.82
  5421.9 1516.35  5456.9 1525.65  5499.0 1525.51  5505.4 1526.61  5549.1 1527.77
#Mann=3,-1,0
  4517.1    0.07       0  4993.8    0.07       0  4998.0    0.07       0
Bank Sta=4993.8,4998
Exp/Cntr=0.3,0.1

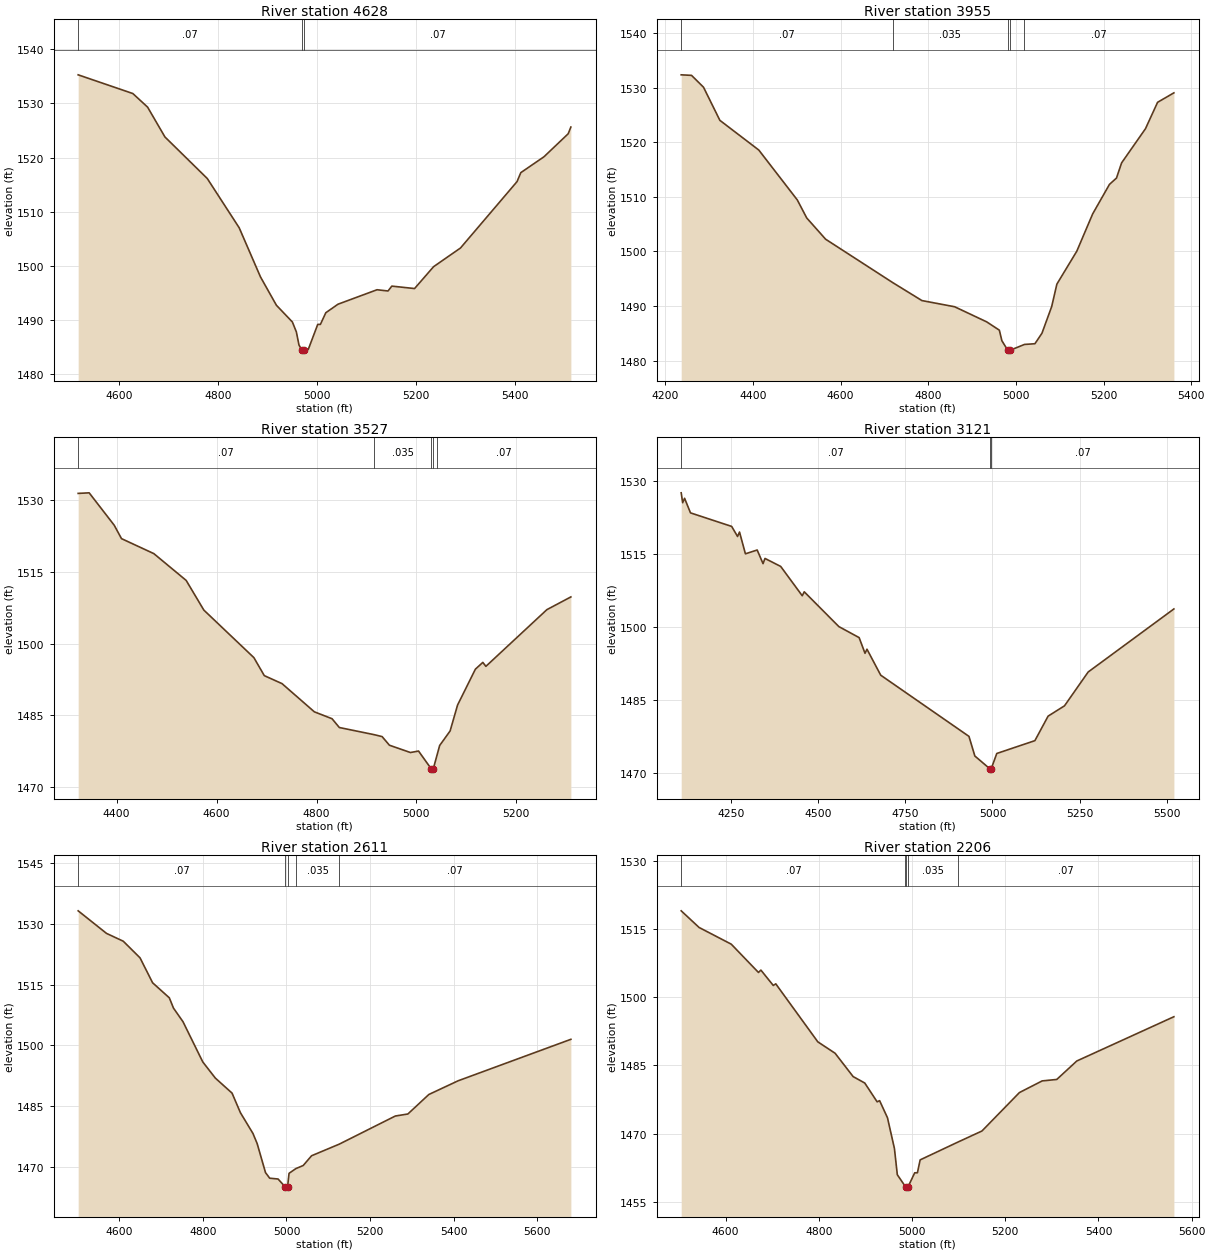
Type RM Length L Ch R = 1,4628,673,673,673
BEGIN DESCRIPTION:
Mapping XS 6b7a2f87
END DESCRIPTION:
XS GIS Cut Line= 3
      1681982.42      7025635.31      1681804.05      7026088.40
      1681619.69      7026562.27
#Sta/Elev= 30
  4518.0 1535.25  4628.4 1531.80  4658.2 1529.30  4693.3 1523.79  4778.8 1516.13
  4843.3 1507.04  4886.3 1497.98  4918.5 1492.75  4950.8 1489.66  4958.8 1487.84
  4964.1 1485.42  4970.2 1484.42  4970.4 1483.92  4974.4 1484.42  4983.0 1484.63
  5002.0 1489.22  5007.4 1489.22  5018.3 1491.37  5042.9 1492.94  5121.8 1495.61
  5144.0 1495.38  5151.7 1496.28  5197.6 1495.83  5236.0 1499.86  5290.4 1503.31
  5404.6 1515.55  5412.3 1517.21  5459.0 1520.13  5508.0 1524.38  5513.4 1525.62
#Mann=3,-1,0
  4518.0    0.07       0  4970.2    0.07       0  4974.4    0.07       0
Bank Sta=4970.2,4974.4
Exp/Cntr=0.3,0.1

Type RM Length L Ch R = 1,3955,428,428,428
BEGIN DESCRIPTION:
Mapping XS e745d9f8
END DESCRIPTION:
XS GIS Cut Line= 3
      1681593.10      7025174.78      1681207.69      7025841.43
      1681041.27      7026153.48
#Sta/Elev= 30
  4236.4 1532.33  4260.0 1532.23  4287.3 1530.06  4324.6 1524.00  4413.4 1518.56
  4501.2 1509.43  4522.7 1506.13  4565.8 1502.24  4718.8 1494.30  4785.4 1491.01
  4860.0 1489.88  4933.2 1487.11  4962.0 1485.59  4967.8 1483.66  4981.4 1481.89
  4981.7 1481.39  4985.7 1481.89  5019.3 1482.98  5043.1 1483.11  5059.2 1485.03
  5081.4 1489.92  5093.2 1494.02  5138.6 1500.04  5174.9 1506.88  5213.1 1512.27
  5229.2 1513.44  5240.8 1516.21  5295.3 1522.47  5322.9 1527.30  5360.1 1529.03
#Mann=5,-1,0
  4236.4    0.07       0  4718.8   0.035       0  4981.4   0.035       0
  4985.7   0.035       0  5019.3    0.07       0
Bank Sta=4981.4,4985.7
Exp/Cntr=0.3,0.1

Type RM Length L Ch R = 1,3527,406,406,406
BEGIN DESCRIPTION:
Mapping XS aab13072
END DESCRIPTION:
XS GIS Cut Line= 3
      1681548.80      7025090.68      1681001.97      7025496.90
      1680751.95      7025671.40
#Sta/Elev= 30
  4323.0 1531.44  4345.0 1531.56  4395.1 1524.79  4409.7 1521.98  4474.4 1518.85
  4539.1 1513.25  4574.5 1507.04  4674.7 1497.09  4695.5 1493.33  4731.0 1491.66
  4795.7 1485.76  4831.1 1484.32  4845.7 1482.48  4915.6 1480.98  4931.3 1480.58
  4945.9 1478.78  4988.0 1477.25  5004.2 1477.56  5029.5 1473.86  5029.8 1473.36
  5033.8 1473.86  5040.7 1476.51  5046.5 1478.72  5067.4 1481.76  5082.3 1487.17
  5118.0 1494.68  5132.9 1496.10  5139.0 1495.27  5261.1 1507.13  5309.1 1509.79
#Mann=5,-1,0
  4323.0    0.07       0  4915.6   0.035       0  5029.5   0.035       0
  5033.8   0.035       0  5040.7    0.07       0
Bank Sta=5029.5,5033.8
Exp/Cntr=0.3,0.1

Type RM Length L Ch R = 1,3121,510,510,510
BEGIN DESCRIPTION:
Mapping XS ed307045
END DESCRIPTION:
XS GIS Cut Line= 3
      1681730.40      7024719.52      1680917.88      7025118.84
      1680716.74      7025583.53
#Sta/Elev= 30
  4108.2 1527.50  4112.4 1525.47  4117.9 1526.38  4134.8 1523.39  4252.8 1520.61
  4269.7 1518.54  4275.3 1519.46  4292.2 1514.99  4325.9 1515.77  4342.7 1512.97
  4348.3 1514.04  4393.3 1512.40  4455.1 1506.38  4460.7 1507.20  4559.9 1500.06
  4618.0 1497.80  4634.9 1494.58  4640.5 1495.42  4679.9 1490.09  4932.7 1477.54
  4949.6 1473.51  4992.3 1470.91  4992.6 1470.41  4996.6 1470.91  5012.4 1474.03
  5121.6 1476.66  5159.5 1481.69  5206.5 1483.81  5274.2 1490.74  5519.9 1503.68
#Mann=3,-1,0
  4108.2    0.07       0  4992.3    0.07       0  4996.6    0.07       0
Bank Sta=4992.3,4996.6
Exp/Cntr=0.3,0.1

Type RM Length L Ch R = 1,2611,405,405,405
BEGIN DESCRIPTION:
Mapping XS 6905941c
END DESCRIPTION:
XS GIS Cut Line= 3
      1680574.88      7024390.17      1680585.30      7024895.34
      1680616.55      7025567.24
#Sta/Elev= 30
  4502.1 1533.27  4569.9 1527.69  4609.9 1525.76  4650.0 1521.65  4680.0 1515.49
  4720.0 1511.77  4730.0 1509.22  4752.7 1505.86  4800.0 1495.92  4830.0 1491.93
  4870.0 1488.21  4890.0 1483.37  4920.0 1478.23  4930.0 1475.74  4950.0 1468.56
  4960.0 1467.18  4980.0 1466.98  4997.5 1464.98  4997.9 1464.48  5002.6 1464.98
  5006.2 1468.38  5022.5 1469.55  5040.1 1470.32  5060.1 1472.73  5126.1 1475.59
  5260.3 1482.55  5290.3 1483.05  5340.4 1487.87  5410.5 1491.26  5680.0 1501.51
#Mann=5,-1,0
  4502.1    0.07       0  4997.5    0.07       0  5002.6    0.07       0
  5022.5   0.035       0  5126.1    0.07       0
Bank Sta=4997.5,5002.6
Exp/Cntr=0.3,0.1

Type RM Length L Ch R = 1,2206,443,443,443
BEGIN DESCRIPTION:
Mapping XS ae9681a0
END DESCRIPTION:
XS GIS Cut Line= 3
      1680057.71      7024517.42      1680213.97      7024994.01
      1680495.19      7025473.12
#Sta/Elev= 30
  4504.8 1519.00  4543.2 1515.34  4612.2 1511.67  4670.6 1505.45  4675.8 1505.97
  4702.4 1502.59  4707.7 1502.95  4797.9 1490.20  4835.0 1487.69  4873.7 1482.56
  4898.7 1481.14  4925.2 1477.01  4930.5 1477.27  4947.4 1473.50  4962.3 1466.75
  4968.5 1460.98  4986.0 1458.36  4986.4 1458.32  4986.8 1457.82  4991.5 1458.32
  5005.8 1461.41  5011.6 1461.41  5017.5 1464.25  5099.1 1468.19  5150.1 1470.60
  5230.5 1479.05  5279.3 1481.61  5310.6 1481.93  5353.6 1485.99  5561.9 1495.72
#Mann=5,-1,0
  4504.8    0.07       0  4986.0   0.035       0  4986.4   0.035       0
  4991.5   0.035       0  5099.1    0.07       0
Bank Sta=4986.4,4991.5
Exp/Cntr=0.3,0.1

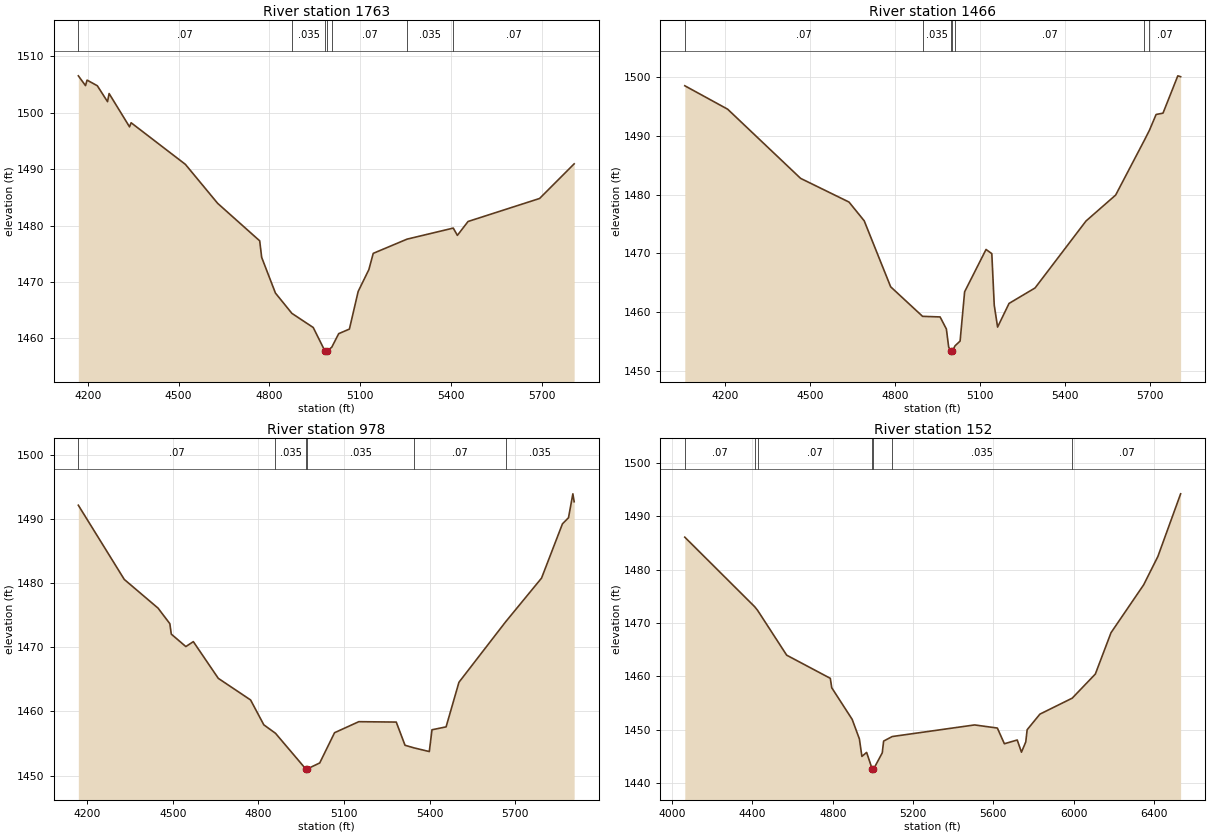
Type RM Length L Ch R = 1,1763,297,297,297
BEGIN DESCRIPTION:
Mapping XS 404b98ad
END DESCRIPTION:
XS GIS Cut Line= 3
      1679622.82      7024392.41      1679851.99      7025191.93
      1680346.81      7025827.38
#Sta/Elev= 30
  4168.9 1506.56  4192.6 1504.83  4197.8 1505.80  4231.6 1504.80  4265.3 1501.98
  4270.5 1503.42  4338.0 1497.51  4343.2 1498.24  4522.4 1490.86  4628.9 1483.95
  4767.7 1477.30  4774.3 1474.36  4819.7 1468.04  4874.0 1464.44  4944.5 1461.93
  4983.6 1457.71  4984.0 1457.21  4988.7 1457.71  5005.7 1458.44  5028.6 1460.84
  5063.9 1461.65  5092.9 1468.33  5128.2 1472.20  5142.6 1475.08  5254.3 1477.60
  5406.9 1479.56  5420.4 1478.27  5455.7 1480.73  5691.8 1484.81  5806.0 1490.95
#Mann=7,-1,0
  4168.9    0.07       0  4874.0   0.035       0  4983.6   0.035       0
  4988.7   0.035       0  5005.7    0.07       0  5254.3   0.035       0
  5406.9    0.07       0
Bank Sta=4983.6,4988.7
Exp/Cntr=0.3,0.1

Type RM Length L Ch R = 1,1466,488,488,488
BEGIN DESCRIPTION:
Mapping XS 2bfdadd2
END DESCRIPTION:
XS GIS Cut Line= 3
      1679474.39      7024301.34      1679573.35      7025249.22
      1679721.78      7026033.06
#Sta/Elev= 30
  4058.2 1498.52  4209.6 1494.53  4467.1 1482.76  4638.0 1478.73  4691.7 1475.54
  4785.1 1464.31  4897.8 1459.28  4959.7 1459.18  4981.9 1457.12  4989.9 1454.07
  4997.4 1453.35  4997.7 1452.85  5002.5 1453.35  5012.4 1454.26  5030.3 1455.07
  5046.3 1463.46  5121.9 1470.66  5142.3 1469.95  5150.9 1461.17  5162.7 1457.45
  5203.2 1461.48  5295.0 1464.11  5475.0 1475.51  5579.6 1479.92  5680.8 1489.23
  5698.9 1490.95  5722.4 1493.63  5746.8 1493.86  5799.1 1500.21  5809.0 1500.06
#Mann=7,-1,0
  4058.2    0.07       0  4897.8   0.035       0  4997.4   0.035       0
  5002.5   0.035       0  5012.4    0.07       0  5680.8   0.035       0
  5698.9    0.07       0
Bank Sta=4997.4,5002.5
Exp/Cntr=0.3,0.1

Type RM Length L Ch R = 1,978,826,826,826
BEGIN DESCRIPTION:
Mapping XS 9d1a6c17
END DESCRIPTION:
XS GIS Cut Line= 3
      1679318.15      7024332.53      1679115.02      7025142.45
      1679590.77      7025909.37
#Sta/Elev= 30
  4169.3 1492.17  4330.4 1480.59  4448.8 1476.11  4490.0 1473.69  4495.1 1472.06
  4546.1 1470.12  4572.3 1470.89  4659.8 1465.16  4772.9 1461.79  4819.3 1457.91
  4860.2 1456.59  4966.2 1451.03  4966.6 1450.53  4971.4 1451.03  5015.2 1451.96
  5067.2 1456.68  5152.2 1458.40  5283.4 1458.34  5314.1 1454.72  5345.9 1454.31
  5399.2 1453.74  5408.6 1457.14  5458.0 1457.59  5503.1 1464.55  5666.3 1473.96
  5792.5 1480.80  5865.7 1489.26  5887.0 1490.22  5902.3 1493.95  5906.8 1492.72
#Mann=6,-1,0
  4169.3    0.07       0  4860.2   0.035       0  4966.2   0.035       0
  4971.4   0.035       0  5345.9    0.07       0  5666.3   0.035       0
Bank Sta=4966.2,4971.4
Exp/Cntr=0.3,0.1

Type RM Length L Ch R = 1,152,0,0,0
BEGIN DESCRIPTION:
Chimney Creek 1182 1.0
END DESCRIPTION:
XS GIS Cut Line= 3
      1679163.88      7024360.65      1678389.76      7024887.50
      1679505.00      7025938.00
#Sta/Elev= 30
  4063.6 1486.06  4411.5 1473.05  4425.7 1472.39  4570.9 1463.98  4788.0 1459.65
  4795.3 1457.88  4896.9 1451.97  4932.9 1448.31  4945.3 1445.04  4968.8 1445.79
  4997.3 1442.60  4997.7 1442.10  5002.5 1442.60  5046.7 1445.71  5053.5 1447.91
  5096.5 1448.76  5506.3 1450.93  5619.6 1450.35  5654.7 1447.41  5718.7 1448.11
  5739.7 1445.83  5761.2 1447.75  5768.0 1450.03  5831.5 1452.95  5992.4 1455.94
  6107.5 1460.45  6185.6 1468.19  6348.2 1477.15  6419.0 1482.46  6532.1 1494.17
#Mann=7,-1,0
  4063.6    0.07       0  4411.5   0.035       0  4425.7    0.07       0
  4997.3    0.07       0  5002.5    0.07       0  5096.5   0.035       0
  5992.4    0.07       0
Bank Sta=4997.3,5002.5
Exp/Cntr=0.3,0.1

Chan Stop Cuts=-1