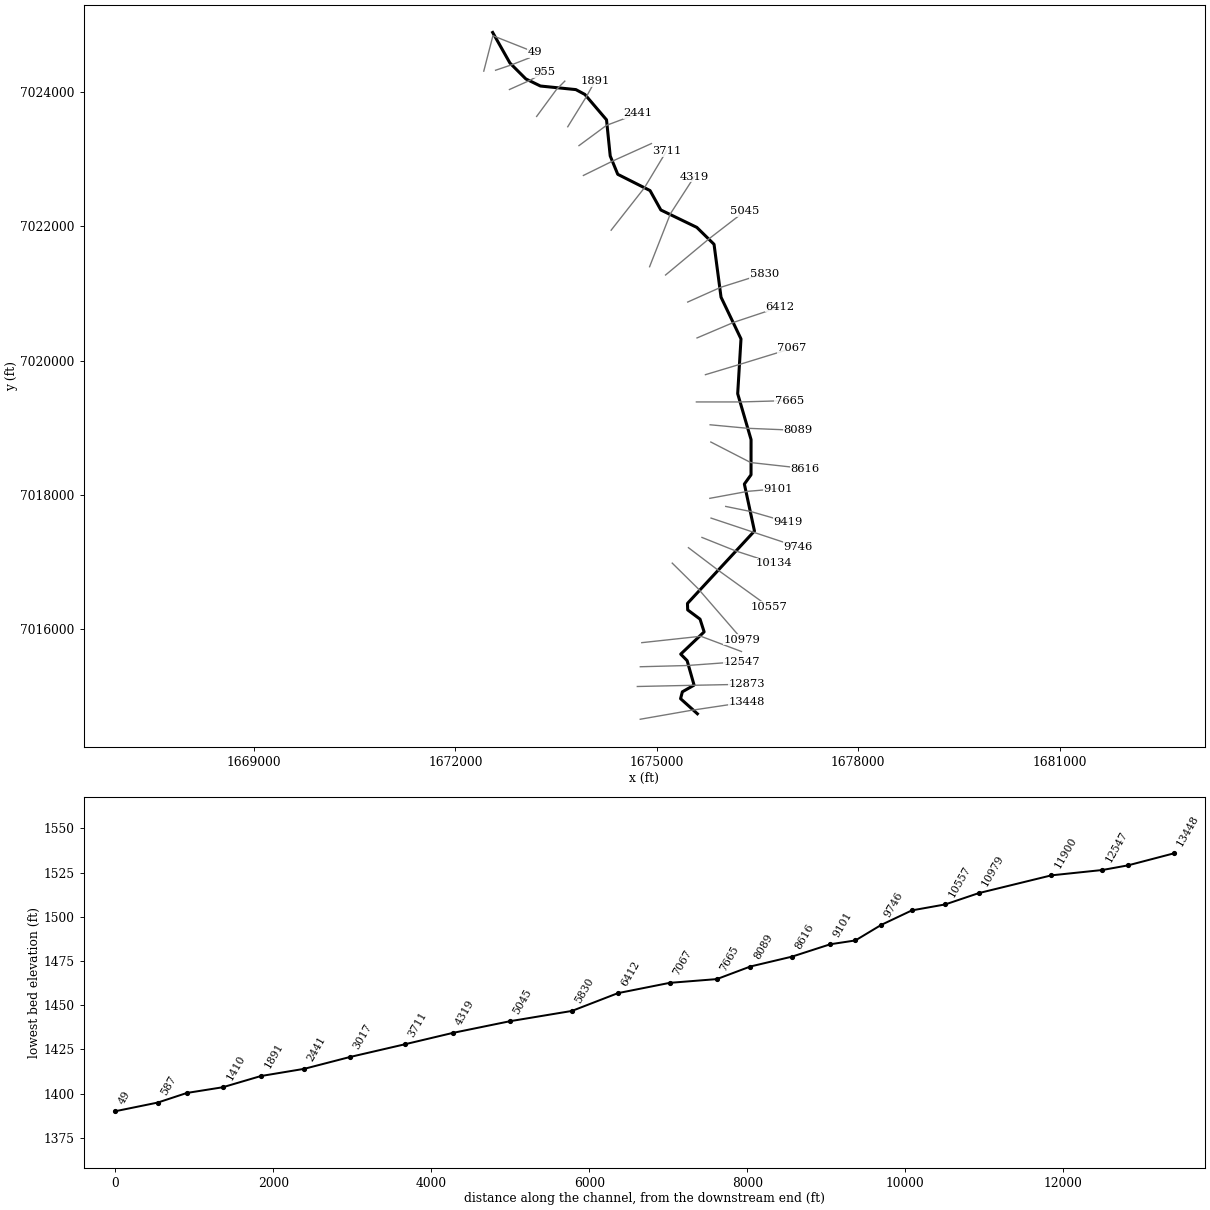
--- Chimney Creek 1183.prj (project) ---

Proj Title=Chimney Creek 1183 Base Level Engineering
Current Plan=p01
Default Exp/Contr=0.3,0.1
English Units
Geom File=g01
Flow File=f01
Plan File=p01
BEGIN DESCRIPTION:
Chimney Creek 1183
END DESCRIPTION:

--- Chimney Creek 1183.p01 (plan) ---

Plan Title=Multiple Run
Short Identifier=Multiple
Geom File=g01
Flow File=f01
Subcritical Flow
K Sum by GR= 0
Std Step Tol= 0.01
Critical Tol= 0.01
Num of Std Step Trials= 20
Max Error Tol= 0.3
Flow Tol Ratio= 0.001
Split Flow NTrial= 30
Split Flow Tol= 0.02
Split Flow Ratio= 0.02
Log Output Level= 0
Friction Slope Method= 1
Unsteady Friction Slope Method= 2
Unsteady Bridges Friction Slope Method= 1
Parabolic Critical Depth
Global Vel Dist=  1 , 1 , 1
Global Log Level= 0
CheckData=True
Encroach Param= -1, 0, 0, 0
BEGIN DESCRIPTION:
Multiple Run
END DESCRIPTION:

--- Chimney Creek 1183.f01 (steady flow) ---

Flow Title=Multiple
Number of Profiles=7
Profile Names=10-year,25-year,50-year,1pct_min,100-year,1pct_plu,500-year
River Rch & RM= Chimney Creek 11,Reach-1,13448
     291     408     505     312     623    1242     957
River Rch & RM= Chimney Creek 11,Reach-1,10979
     384     545     681     424     847    1690    1325
River Rch & RM= Chimney Creek 11,Reach-1,8616
     749    1101    1410     898    1791    3574    2927
River Rch & RM= Chimney Creek 11,Reach-1,2441
     755    1109    1420     904    1804    3599    2946
Boundary for River Rch & Prof#=Chimney Creek 11,Reach-1,1
Up Type=0
Dn Type=3
Dn Slope=0.005
Boundary for River Rch & Prof#=Chimney Creek 11,Reach-1,2
Up Type=0
Dn Type=3
Dn Slope=0.005
Boundary for River Rch & Prof#=Chimney Creek 11,Reach-1,3
Up Type=0
Dn Type=3
Dn Slope=0.005
Boundary for River Rch & Prof#=Chimney Creek 11,Reach-1,4
Up Type=0
Dn Type=3
Dn Slope=0.005
Boundary for River Rch & Prof#=Chimney Creek 11,Reach-1,5
Up Type=0
Dn Type=3
Dn Slope=0.005
Boundary for River Rch & Prof#=Chimney Creek 11,Reach-1,6
Up Type=0
Dn Type=3
Dn Slope=0.005
Boundary for River Rch & Prof#=Chimney Creek 11,Reach-1,7
Up Type=0
Dn Type=3
Dn Slope=0.005

--- Chimney Creek 1183.g01 (geometry) ---

Geom Title=Existing Conditions

River Reach=Chimney Creek 11,Reach-1
Reach XY= 30
      1675605.00      7014738.00      1675354.46      7014962.89
      1675381.01      7015065.18      1675555.55      7015164.98
      1675451.90      7015529.69      1675356.61      7015626.53
      1675705.26      7015958.20      1675644.48      7016147.77
      1675460.30      7016285.33      1675457.14      7016382.03
      1676455.20      7017460.65      1676304.84      7018160.32
      1676403.98      7018298.42      1676404.48      7018822.78
      1676205.21      7019506.27      1676254.49      7020322.79
      1675957.25      7020943.93      1675852.94      7021732.15
      1675596.38      7021984.16      1675060.47      7022243.26
      1674899.74      7022532.53      1674418.61      7022774.76
      1674306.22      7023048.50      1674251.24      7023586.44
      1673928.47      7023964.99      1673794.50      7024036.80
      1673266.97      7024089.96      1673048.94      7024196.14
      1672812.86      7024431.83      1672555.00      7024888.00

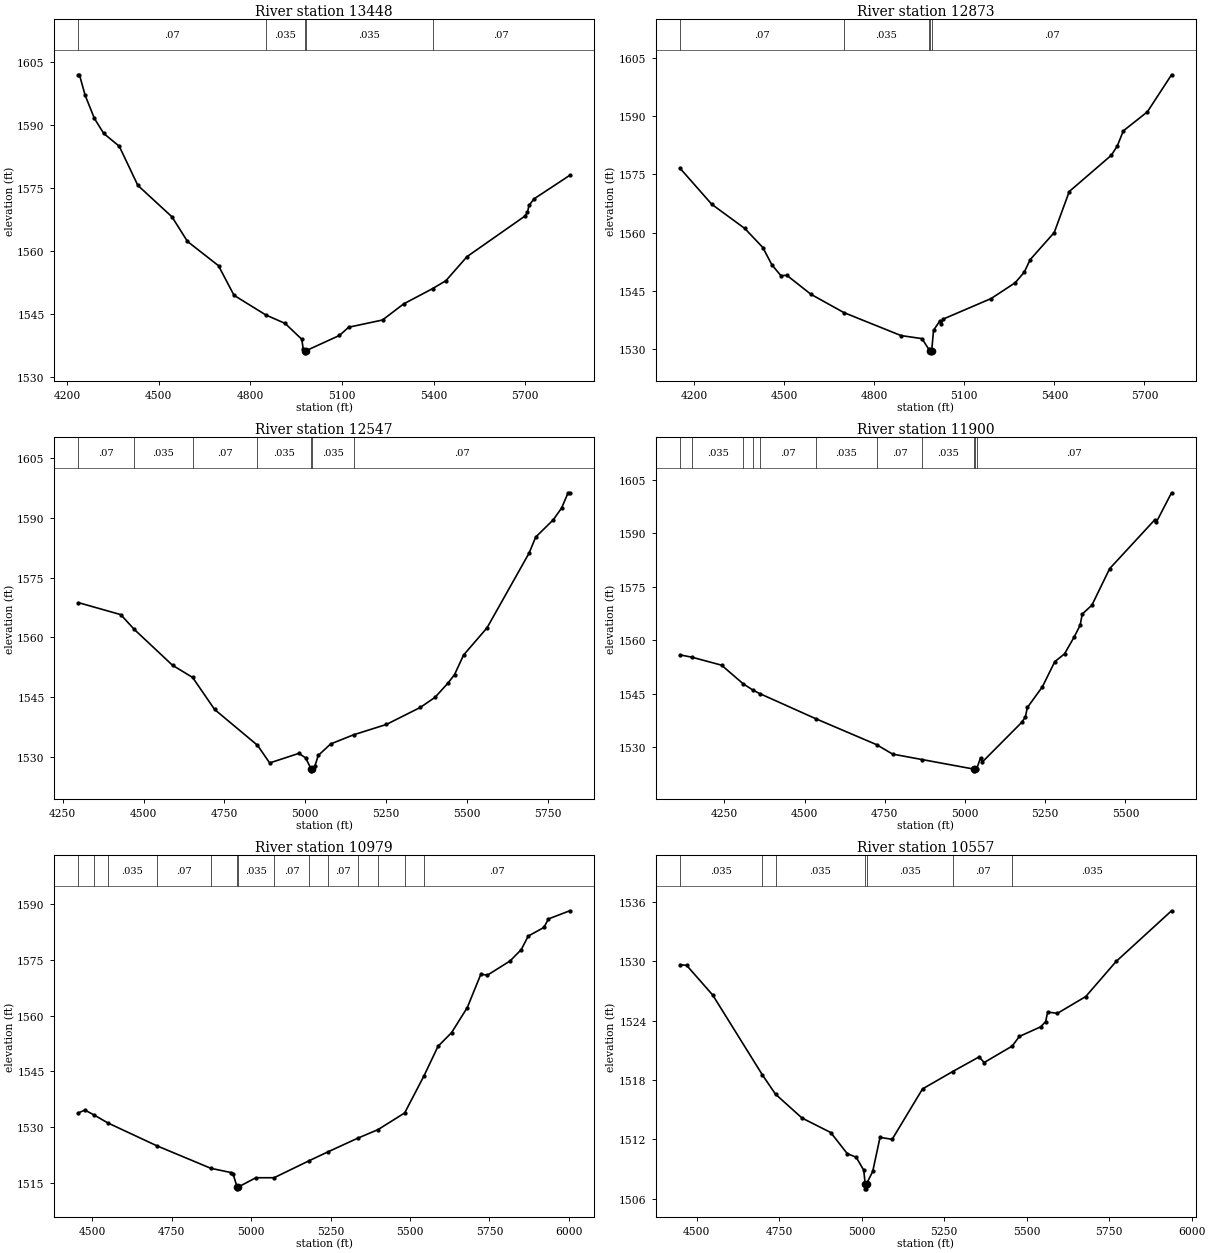
Type RM Length L Ch R = 1,13448,575,575,575
BEGIN DESCRIPTION:
Chimney Creek 1183 29.0
END DESCRIPTION:
XS GIS Cut Line= 3
      1674753.42      7014656.49      1675505.00      7014788.00
      1676340.41      7014912.94
#Sta/Elev= 30
  4237.5 1601.97  4240.9 1601.97  4259.4 1597.10  4289.9 1591.58  4320.3 1588.01
  4371.1 1584.98  4432.0 1575.66  4543.7 1568.18  4594.4 1562.33  4695.9 1556.56
  4746.7 1549.52  4850.7 1544.85  4913.8 1542.84  4968.2 1539.08  4973.3 1536.72
  4978.2 1536.34  4978.4 1535.84  4982.2 1536.34  5091.5 1539.97  5121.8 1541.93
  5232.6 1543.65  5301.8 1547.48  5396.9 1551.13  5440.1 1553.00  5509.3 1558.73
  5698.2 1568.34  5706.8 1569.23  5711.9 1570.89  5728.5 1572.46  5845.2 1578.05
#Mann=5,-1,0
  4237.5    0.07       0  4850.7   0.035       0  4978.2   0.035       0
  4982.2   0.035       0  5396.9    0.07       0
Bank Sta=4978.2,4982.2
Exp/Cntr=0.3,0.1

Type RM Length L Ch R = 1,12873,326,326,326
BEGIN DESCRIPTION:
Mapping XS d2227d65
END DESCRIPTION:
XS GIS Cut Line= 3
      1674710.01      7015144.34      1675556.40      7015162.57
      1676345.46      7015178.20
#Sta/Elev= 30
  4154.3 1576.52  4259.3 1567.31  4369.3 1561.09  4429.4 1556.19  4459.4 1551.75
  4489.4 1548.97  4509.4 1549.04  4589.4 1544.17  4699.2 1539.46  4889.5 1533.55
  4959.5 1532.76  4982.0 1530.00  4987.5 1529.61  4987.7 1529.11  4991.5 1529.61
  4997.7 1534.91  5018.5 1537.29  5023.5 1536.50  5029.5 1537.78  5189.5 1543.07
  5269.5 1547.13  5299.5 1549.82  5319.6 1553.09  5399.6 1560.05  5449.6 1570.59
  5589.6 1579.91  5609.6 1582.32  5629.6 1586.19  5709.6 1591.07  5790.1 1600.61
#Mann=5,-1,0
  4154.3    0.07       0  4699.2   0.035       0  4982.0    0.07       0
  4987.5    0.07       0  4991.5    0.07       0
Bank Sta=4987.5,4991.5
Exp/Cntr=0.3,0.1

Type RM Length L Ch R = 1,12547,647,647,647
BEGIN DESCRIPTION:
Mapping XS b52c5f23
END DESCRIPTION:
XS GIS Cut Line= 3
      1674754.35      7015438.61      1675452.24      7015456.84
      1676269.92      7015516.74
#Sta/Elev= 30
  4298.9 1568.70  4429.6 1565.69  4471.7 1561.96  4589.6 1552.98  4651.8 1549.91
  4719.7 1541.87  4852.2 1532.88  4889.8 1528.44  4979.8 1530.84  5000.9 1529.72
  5017.8 1526.96  5018.1 1526.46  5021.8 1526.96  5029.9 1527.75  5039.9 1530.32
  5078.2 1533.21  5149.1 1535.51  5250.5 1538.11  5355.4 1542.39  5400.9 1544.93
  5441.0 1548.52  5461.0 1550.62  5489.0 1555.55  5561.3 1562.36  5691.6 1581.18
  5711.7 1585.16  5766.3 1589.52  5791.9 1592.48  5811.9 1596.29  5816.9 1596.29
#Mann=7,-1,0
  4298.9    0.07       0  4471.7   0.035       0  4651.8    0.07       0
  4852.2   0.035       0  5017.8   0.035       0  5021.8   0.035       0
  5149.1    0.07       0
Bank Sta=5017.8,5021.8
Exp/Cntr=0.3,0.1

Type RM Length L Ch R = 1,11900,921,921,921
BEGIN DESCRIPTION:
Mapping XS 692785cf
END DESCRIPTION:
XS GIS Cut Line= 3
      1674776.85      7015797.38      1675655.80      7015892.87
      1676261.68      7015665.66
#Sta/Elev= 30
  4112.4 1555.92  4150.1 1555.25  4241.3 1553.04  4308.5 1547.83  4339.0 1546.06
  4360.2 1545.08  4535.6 1538.01  4724.3 1530.77  4774.4 1528.12  4867.0 1526.58
  5026.8 1523.93  5027.1 1523.43  5030.8 1523.93  5036.3 1524.01  5048.4 1527.08
  5053.8 1525.90  5177.2 1537.06  5187.9 1538.52  5194.4 1541.19  5241.3 1547.01
  5279.8 1554.04  5310.1 1556.21  5340.3 1560.96  5358.8 1564.25  5365.3 1567.36
  5395.5 1569.87  5450.7 1580.09  5591.3 1593.78  5596.7 1593.21  5643.6 1601.36
#Mann=11,-1,0
  4112.4    0.07       0  4150.1   0.035       0  4308.5    0.07       0
  4339.0   0.035       0  4360.2    0.07       0  4535.6   0.035       0
  4724.3    0.07       0  4867.0   0.035       0  5026.8   0.035       0
  5030.8   0.035       0  5036.3    0.07       0
Bank Sta=5026.8,5030.8
Exp/Cntr=0.3,0.1

Type RM Length L Ch R = 1,10979,422,422,422
BEGIN DESCRIPTION:
Mapping XS 3481bbe3
END DESCRIPTION:
XS GIS Cut Line= 3
      1675230.20      7016982.25      1675612.98      7016604.68
      1676273.86      7015842.32
#Sta/Elev= 30
  4456.2 1533.84  4476.8 1534.57  4506.6 1533.21  4548.3 1531.14  4702.3 1524.99
  4872.8 1518.90  4936.4 1517.75  4943.4 1517.29  4955.6 1513.86  4955.8 1513.36
  4959.6 1513.86  5014.6 1516.35  5072.1 1516.35  5183.6 1520.98  5242.8 1523.37
  5337.5 1527.08  5399.0 1529.30  5483.2 1533.81  5544.1 1543.81  5588.2 1551.76
  5630.9 1555.45  5680.3 1562.20  5723.0 1571.18  5743.9 1570.94  5815.2 1574.77
  5850.3 1577.83  5872.2 1581.46  5921.5 1583.79  5935.8 1586.08  6002.8 1588.28
#Mann=14,-1,0
  4456.2   0.035       0  4506.6    0.07       0  4548.3   0.035       0
  4702.3    0.07       0  4872.8   0.035       0  4955.6   0.035       0
  4959.6   0.035       0  5072.1    0.07       0  5183.6   0.035       0
  5242.8    0.07       0  5337.5   0.035       0  5399.0    0.07       0
  5483.2   0.035       0  5544.1    0.07       0
Bank Sta=4955.6,4959.6
Exp/Cntr=0.3,0.1

Type RM Length L Ch R = 1,10557,423,423,423
BEGIN DESCRIPTION:
Mapping XS f2bf0ce0
END DESCRIPTION:
XS GIS Cut Line= 3
      1675471.60      7017212.32      1675902.11      7016885.97
      1676671.48      7016331.47
#Sta/Elev= 30
  4450.4 1529.67  4469.7 1529.61  4548.7 1526.61  4698.8 1518.55  4739.1 1516.57
  4819.2 1514.16  4906.4 1512.69  4956.4 1510.56  4983.5 1510.19  5006.5 1508.87
  5010.7 1507.49  5011.0 1506.99  5014.5 1506.99  5014.8 1507.49  5033.6 1508.75
  5055.8 1512.20  5092.5 1512.00  5184.5 1517.10  5275.9 1518.86  5356.3 1520.35
  5371.1 1519.77  5456.4 1521.44  5477.8 1522.41  5542.9 1523.39  5557.6 1523.92
  5563.7 1524.88  5593.2 1524.75  5679.1 1526.45  5771.1 1530.00  5939.0 1535.13
#Mann=7,-1,0
  4450.4   0.035       0  4698.8    0.07       0  4739.1   0.035       0
  5010.7   0.035       0  5014.8   0.035       0  5275.9    0.07       0
  5456.4   0.035       0
Bank Sta=5010.7,5014.8
Exp/Cntr=0.3,0.1

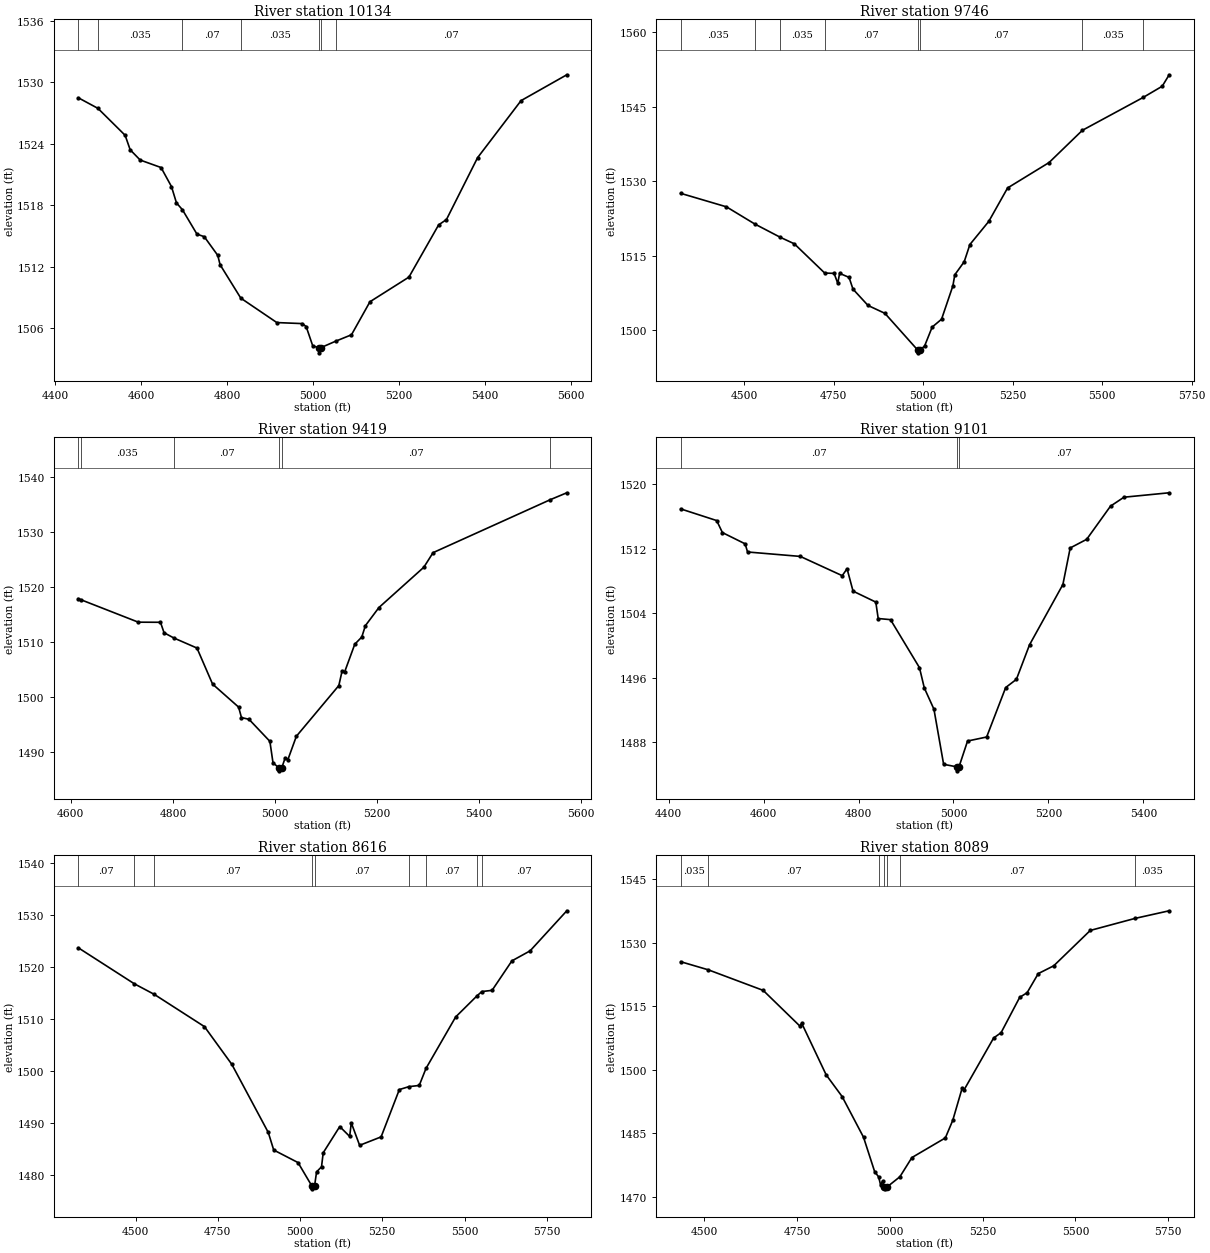
Type RM Length L Ch R = 1,10134,388,388,388
BEGIN DESCRIPTION:
Mapping XS 8364ac3e
END DESCRIPTION:
XS GIS Cut Line= 3
      1675672.91      7017365.15      1676176.42      7017163.74
      1676741.22      7016980.10
#Sta/Elev= 30
  4453.9 1528.47  4499.5 1527.44  4562.9 1524.81  4574.6 1523.40  4597.9 1522.40
  4646.4 1521.67  4670.6 1519.82  4682.3 1518.22  4696.1 1517.56  4729.9 1515.18
  4746.9 1514.93  4778.3 1513.11  4783.7 1512.20  4831.9 1508.94  4915.7 1506.56
  4974.9 1506.46  4983.9 1506.17  4999.3 1504.28  5013.7 1504.11  5013.9 1503.61
  5017.8 1504.11  5052.3 1504.74  5089.3 1505.37  5132.3 1508.59  5222.9 1510.99
  5292.0 1516.08  5310.2 1516.60  5382.6 1522.63  5483.7 1528.19  5590.1 1530.71
#Mann=7,-1,0
  4453.9    0.07       0  4499.5   0.035       0  4696.1    0.07       0
  4831.9   0.035       0  5013.7   0.035       0  5017.8   0.035       0
  5052.3    0.07       0
Bank Sta=5013.7,5017.8
Exp/Cntr=0.3,0.1

Type RM Length L Ch R = 1,9746,327,327,327
BEGIN DESCRIPTION:
Mapping XS 5ff7ca7f
END DESCRIPTION:
XS GIS Cut Line= 3
      1675808.33      7017653.34      1676443.78      7017441.52
      1677103.54      7017222.76
#Sta/Elev= 30
  4322.3 1527.53  4450.2 1524.81  4529.7 1521.34  4600.5 1518.68  4639.9 1517.36
  4724.8 1511.47  4751.0 1511.41  4761.2 1509.41  4766.4 1511.41  4792.8 1510.60
  4803.7 1508.24  4845.8 1504.94  4892.9 1503.36  4985.3 1495.90  4985.7 1495.40
  4990.2 1495.90  5003.9 1496.79  5025.0 1500.59  5051.2 1502.17  5082.9 1508.90
  5088.2 1511.12  5114.5 1513.75  5130.4 1517.22  5183.2 1521.88  5235.7 1528.61
  5351.6 1533.73  5444.6 1540.22  5614.4 1546.84  5667.7 1549.10  5687.2 1551.41
#Mann=8,-1,0
  4322.3   0.035       0  4529.7    0.07       0  4600.5   0.035       0
  4724.8    0.07       0  4985.3    0.07       0  4990.2    0.07       0
  5444.6   0.035       0  5614.4    0.07       0
Bank Sta=4985.3,4990.2
Exp/Cntr=0.3,0.1

Type RM Length L Ch R = 1,9419,318,318,318
BEGIN DESCRIPTION:
Mapping XS bfd81d57
END DESCRIPTION:
XS GIS Cut Line= 3
      1676027.11      7017826.94      1676402.11      7017750.55
      1676954.17      7017590.83
#Sta/Elev= 30
  4614.6 1517.89  4620.0 1517.69  4732.2 1513.62  4775.7 1513.60  4782.7 1511.70
  4802.1 1510.74  4847.2 1508.92  4877.8 1502.37  4928.8 1498.19  4934.4 1496.29
  4949.2 1495.97  4990.1 1491.97  4996.2 1488.08  5008.2 1487.11  5008.6 1486.61
  5013.2 1487.11  5020.2 1489.00  5025.4 1488.65  5042.0 1492.89  5125.2 1502.10
  5131.4 1504.66  5136.6 1504.58  5156.5 1509.62  5170.2 1510.92  5177.3 1512.99
  5203.8 1516.28  5291.8 1523.60  5309.9 1526.25  5539.8 1535.88  5572.0 1537.13
#Mann=6,-1,0
  4614.6    0.07       0  4620.0   0.035       0  4802.1    0.07       0
  5008.2    0.07       0  5013.2    0.07       0  5539.8   0.035       0
Bank Sta=5008.2,5013.2
Exp/Cntr=0.3,0.1

Type RM Length L Ch R = 1,9101,485,485,485
BEGIN DESCRIPTION:
Mapping XS 7f51945d
END DESCRIPTION:
XS GIS Cut Line= 3
      1675790.31      7017947.67      1676355.60      7018051.84
      1676808.11      7018090.90
#Sta/Elev= 30
  4425.4 1516.97  4501.3 1515.52  4513.3 1514.03  4561.2 1512.63  4566.3 1511.62
  4677.4 1511.07  4765.7 1508.68  4775.9 1509.54  4788.5 1506.76  4836.4 1505.40
  4841.5 1503.36  4867.4 1503.22  4928.4 1497.26  4938.6 1494.74  4958.9 1492.10
  4979.3 1485.26  5006.7 1484.95  5007.1 1484.45  5011.7 1484.95  5029.7 1488.15
  5069.9 1488.65  5110.0 1494.79  5132.6 1495.81  5160.2 1500.09  5230.5 1507.58
  5245.9 1512.12  5280.6 1513.19  5330.8 1517.31  5359.2 1518.42  5454.4 1518.97
#Mann=3,-1,0
  4425.4    0.07       0  5006.7    0.07       0  5011.7    0.07       0
Bank Sta=5006.7,5011.7
Exp/Cntr=0.3,0.1

Type RM Length L Ch R = 1,8616,527,527,527
BEGIN DESCRIPTION:
Mapping XS 08aa8cfe
END DESCRIPTION:
XS GIS Cut Line= 3
      1675805.16      7018786.44      1676398.93      7018480.87
      1677210.75      7018390.67
#Sta/Elev= 30
  4326.1 1523.70  4496.4 1516.79  4557.0 1514.76  4709.5 1508.57  4792.6 1501.34
  4903.5 1488.26  4920.0 1484.89  4993.9 1482.48  5036.4 1477.94  5036.9 1477.44
  5044.0 1477.94  5050.3 1480.70  5065.3 1481.67  5070.4 1484.36  5120.7 1489.39
  5150.8 1487.50  5155.8 1490.10  5181.1 1485.79  5246.4 1487.41  5301.8 1496.49
  5330.8 1497.05  5362.2 1497.28  5382.8 1500.55  5472.9 1510.42  5537.7 1514.47
  5552.5 1515.30  5583.6 1515.53  5643.9 1521.19  5699.2 1523.11  5810.7 1530.80
#Mann=9,-1,0
  4326.1    0.07       0  4496.4   0.035       0  4557.0    0.07       0
  5036.4    0.07       0  5044.0    0.07       0  5330.8   0.035       0
  5382.8    0.07       0  5537.7   0.035       0  5552.5    0.07       0
Bank Sta=5036.4,5044
Exp/Cntr=0.3,0.1

Type RM Length L Ch R = 1,8089,424,424,424
BEGIN DESCRIPTION:
Mapping XS 5fd98d20
END DESCRIPTION:
XS GIS Cut Line= 3
      1675794.78      7019043.37      1676350.32      7018991.29
      1677107.30      7018960.04
#Sta/Elev= 30
  4437.0 1525.48  4511.5 1523.56  4659.2 1518.71  4758.0 1510.29  4763.0 1510.95
  4828.9 1498.76  4871.8 1493.65  4929.4 1484.05  4959.5 1475.90  4970.1 1474.69
  4975.6 1472.72  4980.6 1473.68  4985.6 1472.36  4986.1 1471.86  4993.7 1472.36
  5027.5 1474.72  5059.7 1479.24  5149.8 1483.88  5169.8 1488.04  5195.4 1495.73
  5200.4 1495.25  5279.9 1507.48  5299.9 1508.72  5350.0 1517.06  5370.0 1518.16
  5400.0 1522.67  5441.7 1524.51  5540.1 1532.86  5660.1 1535.69  5752.6 1537.50
#Mann=7,-1,0
  4437.0   0.035       0  4511.5    0.07       0  4970.1   0.035       0
  4985.6   0.035       0  4993.7   0.035       0  5027.5    0.07       0
  5660.1   0.035       0
Bank Sta=4985.6,4993.7
Exp/Cntr=0.3,0.1

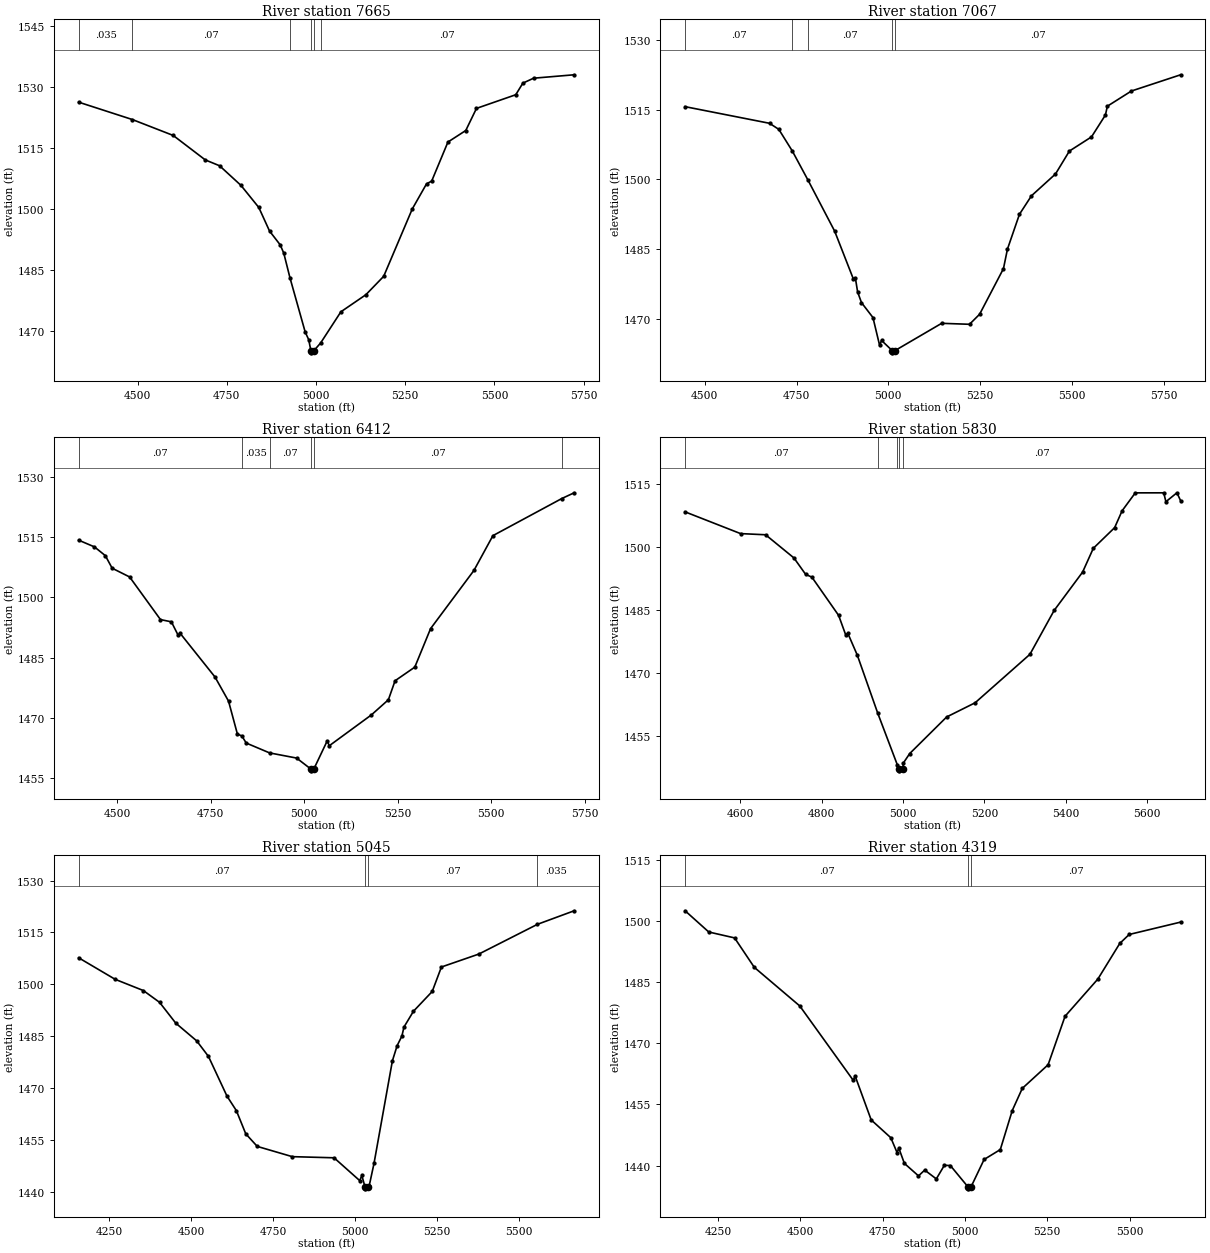
Type RM Length L Ch R = 1,7665,598,598,598
BEGIN DESCRIPTION:
Mapping XS 439380dd
END DESCRIPTION:
XS GIS Cut Line= 3
      1675589.86      7019383.65      1676253.10      7019383.65
      1676978.76      7019404.48
#Sta/Elev= 30
  4334.5 1526.27  4485.2 1522.00  4599.6 1518.10  4689.6 1512.09  4729.6 1510.66
  4789.6 1505.84  4839.6 1500.42  4869.6 1494.65  4899.6 1491.24  4909.6 1489.21
  4926.9 1483.18  4969.6 1469.86  4979.6 1467.95  4985.6 1465.24  4986.1 1464.74
  4993.7 1465.24  5013.0 1467.17  5069.7 1474.81  5139.7 1479.00  5189.7 1483.52
  5269.8 1500.05  5309.8 1506.22  5324.2 1506.89  5369.8 1516.48  5419.8 1519.31
  5449.8 1524.74  5559.9 1528.09  5579.9 1530.94  5609.9 1532.15  5723.7 1532.99
#Mann=6,-1,0
  4334.5   0.035       0  4485.2    0.07       0  4926.9   0.035       0
  4985.6   0.035       0  4993.7   0.035       0  5013.0    0.07       0
Bank Sta=4985.6,4993.7
Exp/Cntr=0.3,0.1

Type RM Length L Ch R = 1,7067,655,655,655
BEGIN DESCRIPTION:
Mapping XS 8bfdb48a
END DESCRIPTION:
XS GIS Cut Line= 3
      1675724.75      7019789.71      1676253.44      7019948.58
      1677016.51      7020182.97
#Sta/Elev= 30
  4446.3 1515.64  4676.3 1512.06  4701.7 1510.75  4738.6 1506.07  4781.7 1499.74
  4853.8 1488.83  4905.1 1478.46  4910.3 1478.72  4916.4 1475.73  4926.9 1473.43
  4958.2 1470.21  4976.4 1464.20  4981.6 1465.28  5010.4 1463.11  5010.9 1462.61
  5018.6 1463.11  5145.4 1468.97  5221.3 1468.76  5248.8 1470.92  5313.8 1480.75
  5324.7 1484.96  5357.4 1492.46  5390.1 1496.44  5455.6 1501.14  5493.5 1506.08
  5553.7 1509.13  5591.7 1513.85  5596.9 1515.74  5662.4 1519.01  5796.6 1522.51
#Mann=5,-1,0
  4446.3    0.07       0  4738.6   0.035       0  4781.7    0.07       0
  5010.4    0.07       0  5018.6    0.07       0
Bank Sta=5010.4,5018.6
Exp/Cntr=0.3,0.1

Type RM Length L Ch R = 1,6412,582,582,582
BEGIN DESCRIPTION:
Mapping XS b5287962
END DESCRIPTION:
XS GIS Cut Line= 3
      1675599.52      7020337.12      1676151.62      7020571.50
      1676839.14      7020800.67
#Sta/Elev= 30
  4397.3 1514.25  4439.6 1512.57  4468.7 1510.39  4486.9 1507.26  4533.6 1505.08
  4616.1 1494.46  4645.2 1493.91  4663.4 1490.54  4668.8 1491.02  4761.8 1480.16
  4798.0 1474.15  4821.7 1465.94  4833.5 1465.49  4845.3 1463.71  4907.6 1461.26
  4979.9 1459.97  5017.3 1457.29  5017.8 1456.79  5026.2 1457.29  5061.9 1464.29
  5067.1 1463.03  5179.8 1470.72  5225.2 1474.49  5243.1 1479.23  5295.8 1482.62
  5338.0 1492.21  5453.9 1506.71  5504.6 1515.37  5688.8 1524.62  5721.8 1526.05
#Mann=6,-1,0
  4397.3    0.07       0  4833.5   0.035       0  4907.6    0.07       0
  5017.3    0.07       0  5026.2    0.07       0  5688.8   0.035       0
Bank Sta=5017.3,5026.2
Exp/Cntr=0.3,0.1

Type RM Length L Ch R = 1,5830,785,785,785
BEGIN DESCRIPTION:
Mapping XS f554465d
END DESCRIPTION:
XS GIS Cut Line= 3
      1675460.68      7020871.86      1675950.23      7021090.59
      1676599.58      7021295.47
#Sta/Elev= 30
  4464.8 1508.46  4601.0 1503.28  4662.5 1503.00  4732.1 1497.48  4760.8 1493.57
  4776.2 1492.90  4841.9 1483.78  4859.1 1479.18  4864.6 1479.49  4887.8 1474.29
  4938.0 1460.46  4986.1 1448.15  4990.8 1447.23  4991.3 1446.73  4999.8 1447.23
  5000.9 1448.60  5016.5 1450.85  5107.2 1459.57  5177.1 1462.95  5311.7 1474.50
  5371.2 1484.96  5441.1 1494.10  5467.4 1499.77  5519.8 1504.70  5538.1 1508.71
  5570.5 1512.99  5640.4 1513.00  5645.7 1510.88  5672.8 1513.01  5681.9 1511.11
#Mann=5,-1,0
  4464.8    0.07       0  4938.0   0.035       0  4986.1    0.07       0
  4990.8    0.07       0  4999.8    0.07       0
Bank Sta=4990.8,4999.8
Exp/Cntr=0.3,0.1

Type RM Length L Ch R = 1,5045,726,726,726
BEGIN DESCRIPTION:
Mapping XS 584da4e4
END DESCRIPTION:
XS GIS Cut Line= 3
      1675130.79      7021274.62      1675776.62      7021812.82
      1676307.89      7022222.55
#Sta/Elev= 30
  4156.7 1507.68  4268.2 1501.45  4354.1 1498.21  4403.5 1494.81  4453.0 1488.79
  4516.8 1483.67  4552.7 1479.18  4609.2 1467.71  4637.9 1463.50  4666.5 1456.81
  4701.6 1453.17  4808.4 1450.21  4935.9 1449.88  5014.2 1443.28  5020.6 1444.78
  5030.3 1441.41  5030.8 1440.91  5039.7 1441.41  5043.2 1441.85  5057.7 1448.24
  5113.8 1477.90  5128.3 1482.29  5142.8 1485.06  5149.1 1487.66  5178.1 1492.23
  5235.3 1497.94  5263.3 1505.01  5377.4 1508.75  5556.3 1517.35  5668.3 1521.26
#Mann=4,-1,0
  4156.7    0.07       0  5030.3    0.07       0  5039.7    0.07       0
  5556.3   0.035       0
Bank Sta=5030.3,5039.7
Exp/Cntr=0.3,0.1

Type RM Length L Ch R = 1,4319,608,608,608
BEGIN DESCRIPTION:
Mapping XS 00bd3a68
END DESCRIPTION:
XS GIS Cut Line= 3
      1674892.93      7021398.12      1675202.84      7022187.21
      1675559.61      7022739.30
#Sta/Elev= 30
  4150.1 1502.54  4222.0 1497.33  4300.4 1495.88  4360.2 1488.66  4498.4 1479.17
  4661.1 1460.88  4666.4 1462.01  4715.3 1451.19  4774.9 1446.82  4793.9 1443.17
  4799.3 1444.25  4816.1 1440.52  4859.0 1437.45  4877.9 1438.87  4913.1 1436.71
  4937.5 1440.04  4955.7 1440.00  5009.1 1434.77  5009.6 1434.27  5018.7 1434.77
  5058.3 1441.48  5107.5 1443.91  5143.8 1453.50  5174.2 1458.93  5252.7 1464.74
  5304.1 1476.64  5403.8 1485.78  5470.4 1494.53  5498.9 1496.72  5655.2 1499.76
#Mann=3,-1,0
  4150.1    0.07       0  5009.1    0.07       0  5018.7    0.07       0
Bank Sta=5009.1,5018.7
Exp/Cntr=0.3,0.1

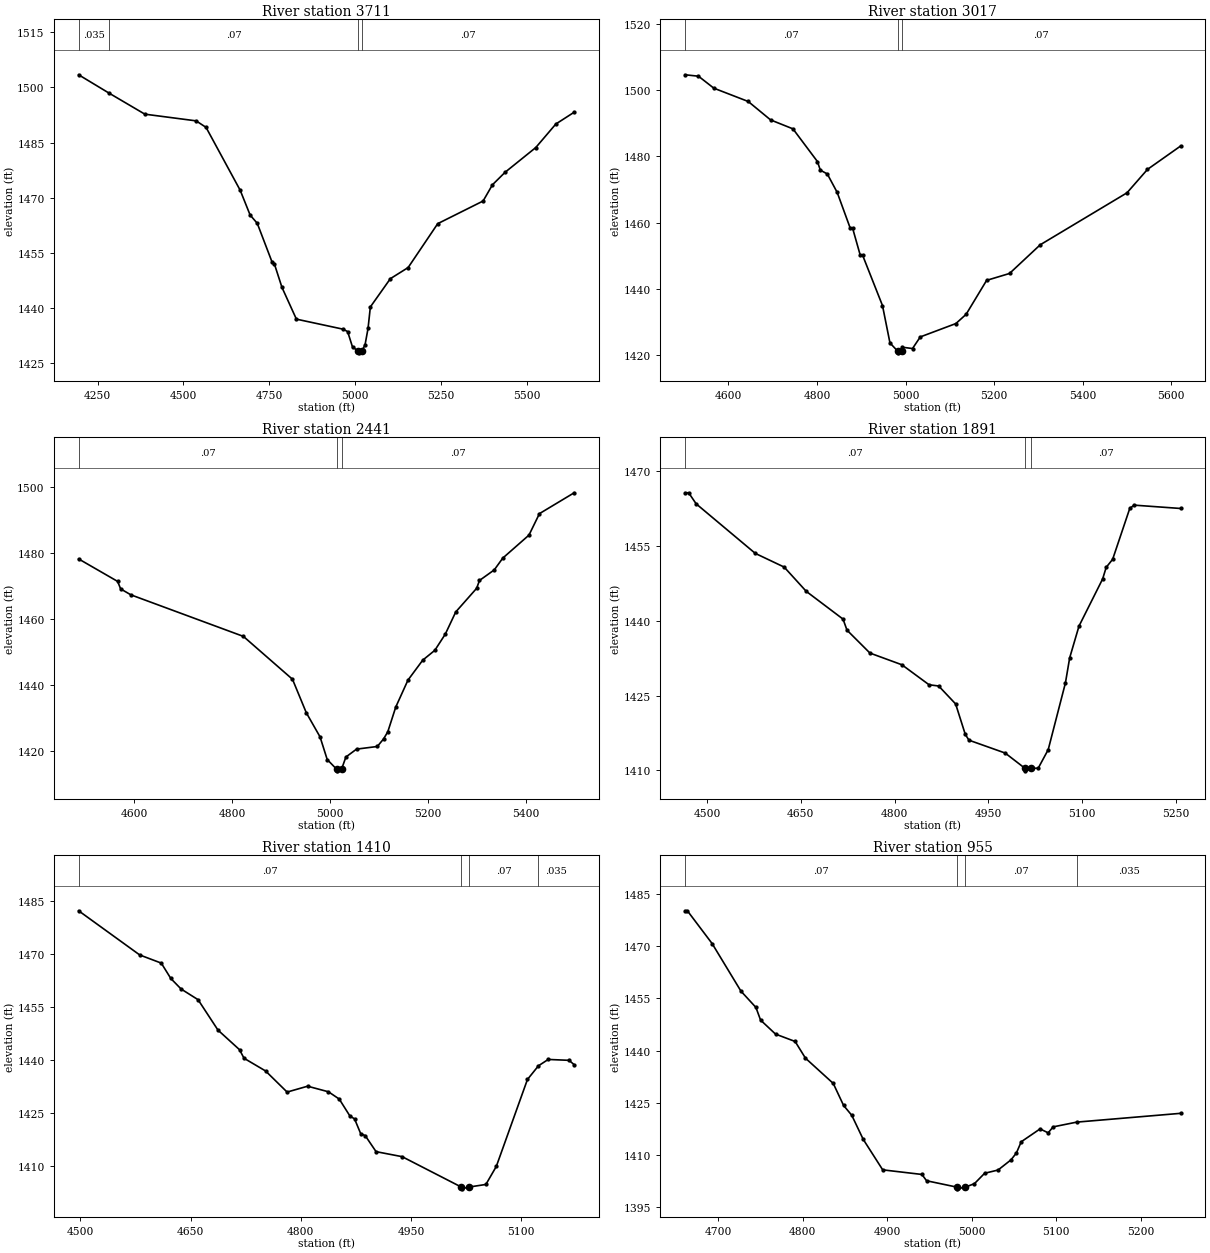
Type RM Length L Ch R = 1,3711,694,694,694
BEGIN DESCRIPTION:
Mapping XS 99129aea
END DESCRIPTION:
XS GIS Cut Line= 3
      1674320.05      7021942.46      1674814.82      7022572.63
      1675145.53      7023122.09
#Sta/Elev= 30
  4194.9 1503.42  4283.3 1498.44  4387.7 1492.71  4536.9 1490.89  4565.8 1489.12
  4665.2 1472.02  4694.1 1465.29  4714.9 1463.03  4758.3 1452.42  4764.6 1452.03
  4786.8 1445.61  4828.8 1436.98  4964.8 1434.25  4978.0 1433.59  4992.2 1429.38
  5009.1 1428.32  5009.6 1427.82  5018.9 1428.32  5028.5 1429.92  5037.4 1434.48
  5044.1 1440.30  5102.3 1447.98  5154.1 1451.01  5240.2 1462.94  5372.3 1469.10
  5399.5 1473.51  5436.4 1476.92  5525.7 1483.64  5584.0 1490.03  5637.4 1493.24
#Mann=4,-1,0
  4194.9   0.035       0  4283.3    0.07       0  5009.1    0.07       0
  5018.9    0.07       0
Bank Sta=5009.1,5018.9
Exp/Cntr=0.3,0.1

Type RM Length L Ch R = 1,3017,576,576,576
BEGIN DESCRIPTION:
Mapping XS 02cbaaed
END DESCRIPTION:
XS GIS Cut Line= 3
      1673906.79      7022757.72      1674351.27      7022976.49
      1674919.87      7023233.05
#Sta/Elev= 30
  4502.0 1504.66  4532.2 1504.23  4566.9 1500.61  4644.6 1496.59  4695.1 1491.02
  4745.6 1488.32  4800.9 1478.44  4807.4 1475.85  4823.2 1474.69  4845.5 1469.12
  4874.8 1458.37  4880.4 1458.27  4897.3 1450.27  4902.9 1450.13  4947.8 1434.93
  4964.7 1423.63  4982.2 1421.14  4982.7 1420.64  4992.2 1421.14  4992.7 1422.33
  5015.6 1421.94  5033.2 1425.45  5113.6 1429.49  5136.7 1432.28  5183.0 1442.54
  5234.7 1444.62  5304.1 1453.29  5500.1 1469.00  5546.3 1476.07  5621.2 1483.14
#Mann=3,-1,0
  4502.0    0.07       0  4982.2    0.07       0  4992.2    0.07       0
Bank Sta=4982.2,4992.2
Exp/Cntr=0.3,0.1

Type RM Length L Ch R = 1,2441,550,550,550
BEGIN DESCRIPTION:
Mapping XS 3b835c87
END DESCRIPTION:
XS GIS Cut Line= 3
      1673840.84      7023202.17      1674250.58      7023504.27
      1674721.40      7023680.82
#Sta/Elev= 30
  4486.4 1478.11  4566.0 1471.31  4572.2 1469.04  4593.0 1467.25  4822.8 1454.67
  4923.1 1441.69  4951.3 1431.56  4979.4 1424.25  4994.0 1417.40  5013.2 1414.48
  5013.7 1413.98  5023.3 1414.48  5032.2 1418.17  5053.9 1420.55  5096.3 1421.35
  5109.0 1423.62  5117.7 1425.79  5134.0 1433.29  5158.9 1441.44  5189.1 1447.48
  5213.8 1450.46  5235.1 1455.34  5256.5 1462.07  5299.2 1469.23  5304.9 1471.59
  5335.1 1474.79  5352.6 1478.37  5406.0 1485.32  5427.4 1491.82  5498.3 1498.13
#Mann=3,-1,0
  4486.4    0.07       0  5013.2    0.07       0  5023.3    0.07       0
Bank Sta=5013.2,5023.3
Exp/Cntr=0.3,0.1

Type RM Length L Ch R = 1,1891,481,481,481
BEGIN DESCRIPTION:
Chimney Creek 1183 4.0
END DESCRIPTION:
XS GIS Cut Line= 3
      1673673.58      7023483.27      1673955.00      7023938.00
      1674080.02      7024163.04
#Sta/Elev= 30
  4465.0 1465.68  4470.7 1465.68  4482.7 1463.46  4577.2 1453.52  4623.4 1450.77
  4658.7 1445.90  4717.5 1440.33  4723.8 1438.12  4760.5 1433.52  4811.6 1431.17
  4855.0 1427.16  4870.4 1426.91  4897.5 1423.31  4912.9 1417.21  4918.8 1416.04
  4976.7 1413.46  5008.4 1410.39  5008.9 1409.89  5018.6 1410.39  5029.5 1410.42
  5045.5 1414.14  5073.0 1427.52  5079.8 1432.56  5094.7 1438.93  5132.5 1448.39
  5138.2 1450.72  5148.5 1452.33  5175.9 1462.55  5182.8 1463.20  5257.2 1462.53
#Mann=3,-1,0
  4465.0    0.07       0  5008.4    0.07       0  5018.6    0.07       0
Bank Sta=5008.4,5018.6
Exp/Cntr=0.3,0.1

Type RM Length L Ch R = 1,1410,455,455,455
BEGIN DESCRIPTION:
Chimney Creek 1183 3.0
END DESCRIPTION:
XS GIS Cut Line= 3
      1673210.04      7023636.92      1673505.00      7024038.00
      1673629.97      7024162.97
#Sta/Elev= 30
  4497.6 1482.21  4580.8 1469.71  4610.1 1467.41  4623.1 1463.06  4637.1 1460.08
  4660.2 1457.06  4687.3 1448.46  4716.6 1442.92  4722.8 1440.49  4752.1 1436.90
  4781.4 1430.93  4809.3 1432.59  4837.7 1431.01  4852.4 1428.95  4867.0 1424.13
  4873.2 1423.36  4881.6 1419.16  4887.8 1418.60  4902.5 1414.08  4938.0 1412.66
  5018.6 1404.06  5019.1 1403.56  5028.8 1404.06  5052.0 1404.80  5066.2 1409.90
  5108.6 1434.50  5123.6 1438.37  5136.9 1440.16  5165.2 1439.91  5172.2 1438.68
#Mann=4,-1,0
  4497.6    0.07       0  5018.6    0.07       0  5028.8    0.07       0
  5123.6   0.035       0
Bank Sta=5018.6,5028.8
Exp/Cntr=0.3,0.1

Type RM Length L Ch R = 1,955,368,368,368
BEGIN DESCRIPTION:
Chimney Creek 1183 2.0
END DESCRIPTION:
XS GIS Cut Line= 3
      1672805.04      7024038.02      1673114.53      7024176.85
      1673330.04      7024297.74
#Sta/Elev= 30
  4660.8 1480.13  4663.5 1480.13  4692.8 1470.71  4726.9 1457.06  4744.6 1452.39
  4750.1 1448.76  4767.8 1444.74  4791.0 1442.62  4803.2 1437.83  4836.1 1430.58
  4848.3 1424.27  4858.0 1421.43  4871.5 1414.55  4894.6 1405.78  4941.0 1404.46
  4946.5 1402.65  4982.2 1400.83  4982.7 1400.33  4992.4 1400.83  5003.1 1401.81
  5015.2 1404.80  5031.1 1405.73  5046.4 1408.65  5052.8 1410.63  5058.5 1413.84
  5080.8 1417.53  5090.4 1416.40  5096.2 1418.11  5124.2 1419.48  5247.1 1422.00
#Mann=4,-1,0
  4660.8    0.07       0  4982.2    0.07       0  4992.4    0.07       0
  5124.2   0.035       0
Bank Sta=4982.2,4992.4
Exp/Cntr=0.3,0.1

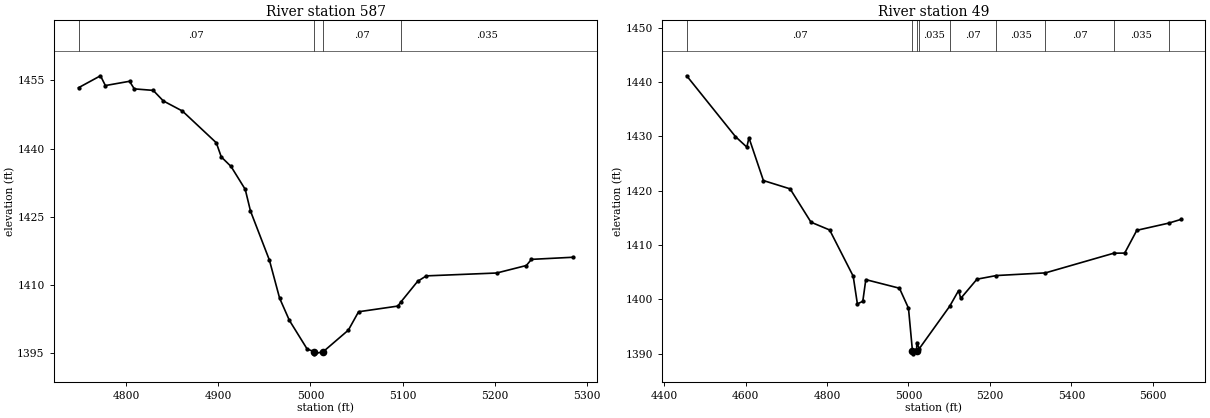
Type RM Length L Ch R = 1,587,538,538,538
BEGIN DESCRIPTION:
Mapping XS 278a3f53
END DESCRIPTION:
XS GIS Cut Line= 3
      1672598.30      7024325.06      1672836.60      7024405.79
      1673101.72      7024509.26
#Sta/Elev= 30
  4748.4 1453.41  4772.2 1456.03  4777.5 1453.88  4803.7 1454.82  4808.9 1453.15
  4829.4 1452.82  4840.4 1450.50  4861.1 1448.28  4897.9 1441.30  4903.3 1438.19
  4913.9 1436.09  4929.3 1431.05  4935.0 1426.29  4955.5 1415.52  4966.6 1407.14
  4977.2 1402.26  4996.5 1395.95  5003.9 1395.40  5004.4 1394.90  5014.1 1395.40
  5041.2 1400.11  5052.3 1404.15  5094.9 1405.40  5098.1 1406.27  5116.4 1410.84
  5125.8 1412.04  5202.2 1412.67  5234.4 1414.32  5239.9 1415.67  5284.6 1416.13
#Mann=4,-1,0
  4748.4    0.07       0  5003.9    0.07       0  5014.1    0.07       0
  5098.1   0.035       0
Bank Sta=5003.9,5014.1
Exp/Cntr=0.3,0.1

Type RM Length L Ch R = 1,49,0,0,0
BEGIN DESCRIPTION:
Chimney Creek 1183 1.0
END DESCRIPTION:
XS GIS Cut Line= 3
      1672422.54      7024311.95      1672558.60      7024839.49
      1673180.20      7024593.26
#Sta/Elev= 30
  4455.2 1441.13  4575.0 1429.95  4603.0 1428.01  4608.2 1429.73  4643.7 1421.86
  4709.3 1420.33  4760.6 1414.20  4806.4 1412.77  4864.2 1404.28  4874.5 1399.18
  4887.8 1399.65  4895.2 1403.64  4977.8 1402.06  5000.0 1398.39  5009.8 1390.49
  5010.3 1389.99  5020.1 1390.49  5020.3 1392.07  5026.6 1390.95  5101.1 1398.73
  5123.0 1401.62  5128.4 1400.19  5168.2 1403.72  5215.9 1404.39  5336.4 1404.88
  5504.3 1408.50  5531.0 1408.52  5560.8 1412.71  5639.1 1414.03  5668.6 1414.70
#Mann=9,-1,0
  4455.2    0.07       0  5009.8    0.07       0  5020.1    0.07       0
  5026.6   0.035       0  5101.1    0.07       0  5215.9   0.035       0
  5336.4    0.07       0  5504.3   0.035       0  5639.1    0.07       0
Bank Sta=5009.8,5020.1
Exp/Cntr=0.3,0.1

Chan Stop Cuts=-1