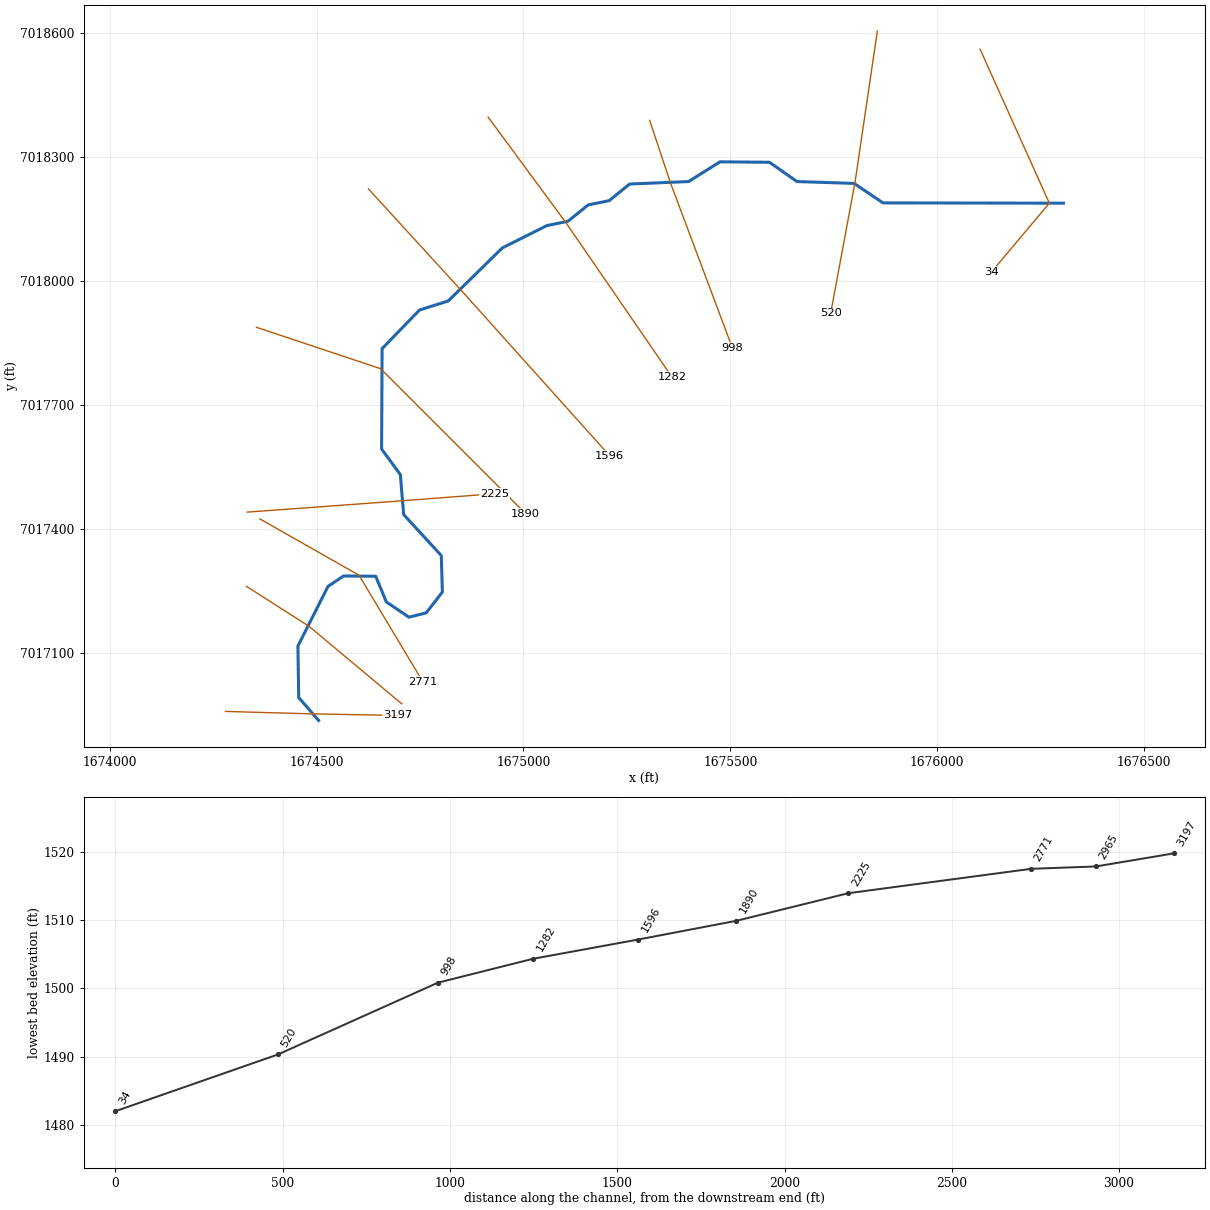
--- Chimney Creek 1184.prj (project) ---

Proj Title=Chimney Creek 1184 Base Level Engineering
Current Plan=p01
Default Exp/Contr=0.3,0.1
English Units
Geom File=g01
Flow File=f01
Plan File=p01
BEGIN DESCRIPTION:
Chimney Creek 1184
END DESCRIPTION:

--- Chimney Creek 1184.p01 (plan) ---

Plan Title=Multiple Run
Short Identifier=Multiple
Geom File=g01
Flow File=f01
Subcritical Flow
K Sum by GR= 0
Std Step Tol= 0.01
Critical Tol= 0.01
Num of Std Step Trials= 20
Max Error Tol= 0.3
Flow Tol Ratio= 0.001
Split Flow NTrial= 30
Split Flow Tol= 0.02
Split Flow Ratio= 0.02
Log Output Level= 0
Friction Slope Method= 1
Unsteady Friction Slope Method= 2
Unsteady Bridges Friction Slope Method= 1
Parabolic Critical Depth
Global Vel Dist=  1 , 1 , 1
Global Log Level= 0
CheckData=True
Encroach Param= -1, 0, 0, 0
BEGIN DESCRIPTION:
Multiple Run
END DESCRIPTION:

--- Chimney Creek 1184.f01 (steady flow) ---

Flow Title=Multiple
Number of Profiles=7
Profile Names=10-year,25-year,50-year,1pct_min,100-year,1pct_plu,500-year
River Rch & RM= Chimney Creek 11,Reach-1,3197
     295     413     512     317     632    1261     973
River Rch & RM= Chimney Creek 11,Reach-1,1890
     302     423     524     323     645    1287     991
Boundary for River Rch & Prof#=Chimney Creek 11,Reach-1,1
Up Type=0
Dn Type=3
Dn Slope=0.005
Boundary for River Rch & Prof#=Chimney Creek 11,Reach-1,2
Up Type=0
Dn Type=3
Dn Slope=0.005
Boundary for River Rch & Prof#=Chimney Creek 11,Reach-1,3
Up Type=0
Dn Type=3
Dn Slope=0.005
Boundary for River Rch & Prof#=Chimney Creek 11,Reach-1,4
Up Type=0
Dn Type=3
Dn Slope=0.005
Boundary for River Rch & Prof#=Chimney Creek 11,Reach-1,5
Up Type=0
Dn Type=3
Dn Slope=0.005
Boundary for River Rch & Prof#=Chimney Creek 11,Reach-1,6
Up Type=0
Dn Type=3
Dn Slope=0.005
Boundary for River Rch & Prof#=Chimney Creek 11,Reach-1,7
Up Type=0
Dn Type=3
Dn Slope=0.005

--- Chimney Creek 1184.g01 (geometry) ---

Geom Title=Existing Conditions

River Reach=Chimney Creek 11,Reach-1
Reach XY= 30
      1674505.00      7016938.00      1674456.99      7016993.38
      1674455.04      7017117.97      1674527.82      7017261.99
      1674565.44      7017287.18      1674643.11      7017286.47
      1674668.60      7017224.56      1674723.38      7017187.57
      1674765.05      7017198.01      1674804.13      7017248.29
      1674801.53      7017336.49      1674710.54      7017435.58
      1674702.64      7017532.02      1674657.26      7017593.94
      1674658.53      7017836.55      1674748.93      7017929.85
      1674818.21      7017951.63      1674948.94      7018079.86
      1675056.72      7018133.84      1675107.20      7018144.08
      1675156.72      7018183.84      1675207.18      7018194.12
      1675256.56      7018234.24      1675399.06      7018240.27
      1675475.04      7018287.95      1675594.49      7018286.79
      1675660.94      7018240.27      1675799.06      7018235.73
      1675868.92      7018188.68      1676305.00      7018188.00

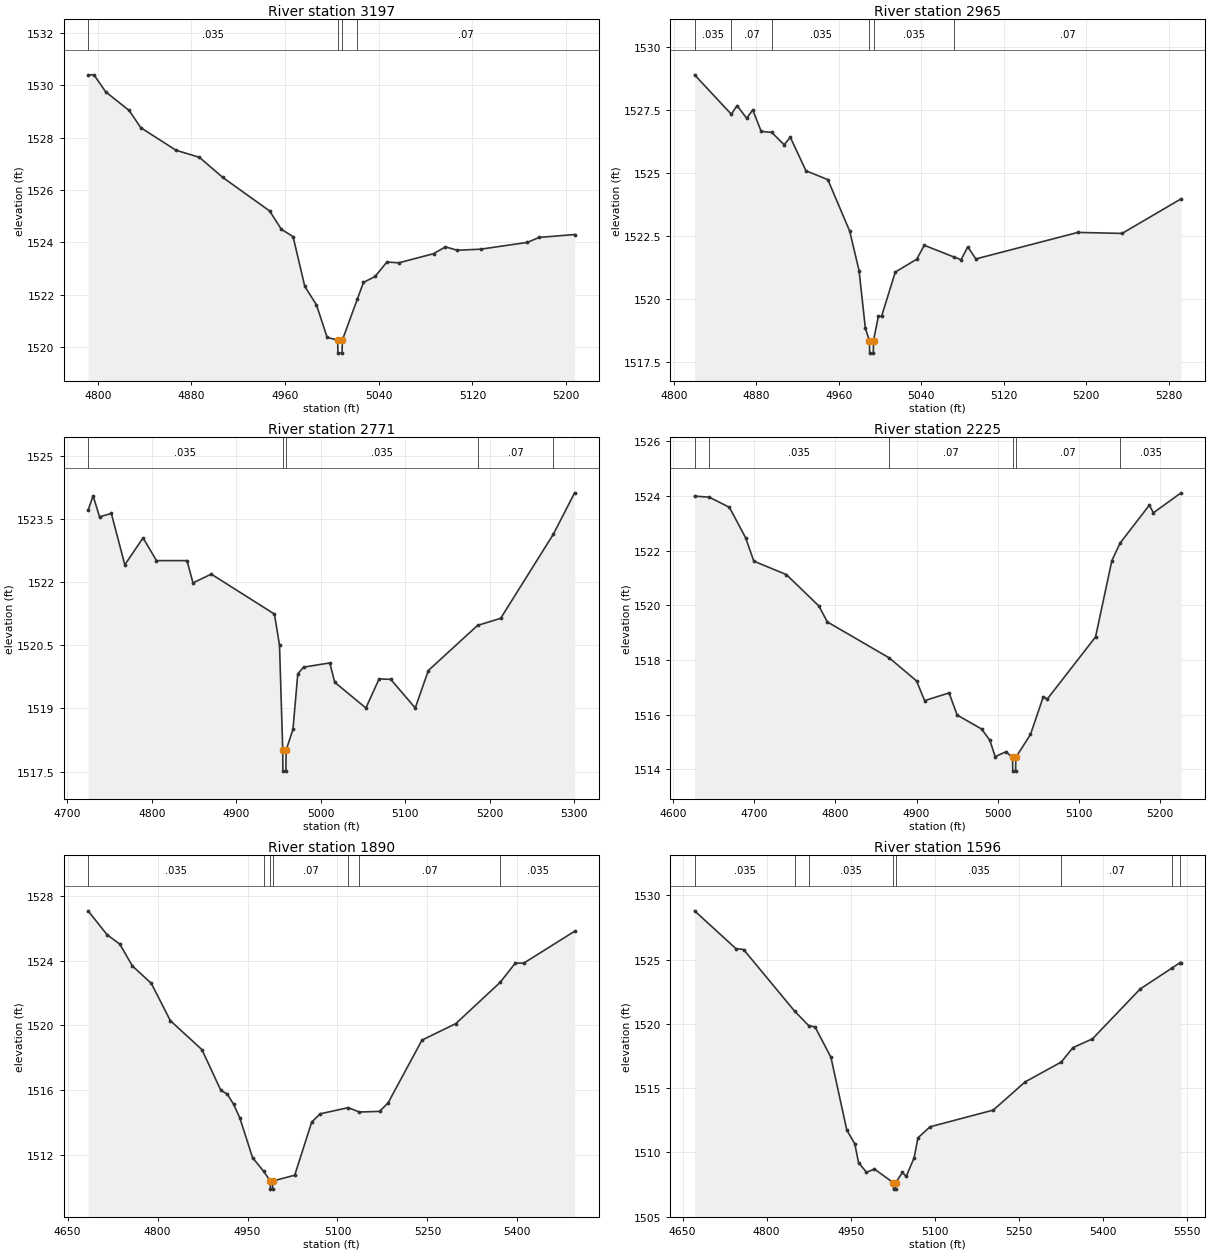
Type RM Length L Ch R = 1,3197,232,232,232
BEGIN DESCRIPTION:
Chimney Creek 1184 5.0
END DESCRIPTION:
XS GIS Cut Line= 3
      1674280.03      7016959.85      1674488.15      7016953.97
      1674695.31      7016950.13
#Sta/Elev= 30
  4791.8 1530.40  4796.8 1530.40  4806.8 1529.75  4826.8 1529.04  4836.8 1528.38
  4866.8 1527.52  4886.8 1527.25  4906.8 1526.48  4946.8 1525.20  4956.8 1524.50
  4966.8 1524.22  4976.8 1522.32  4986.8 1521.61  4995.9 1520.37  5004.9 1520.27
  5005.1 1519.77  5008.6 1519.77  5008.9 1520.27  5021.8 1521.85  5026.9 1522.47
  5036.9 1522.70  5046.9 1523.25  5057.1 1523.22  5086.9 1523.57  5096.9 1523.83
  5106.9 1523.70  5126.9 1523.74  5166.9 1524.00  5176.9 1524.19  5207.2 1524.30
#Mann=4,-1,0
  4791.8   0.035       0  5004.9   0.035       0  5008.9   0.035       0
  5021.8    0.07       0
Bank Sta=5004.9,5008.9
Exp/Cntr=0.3,0.1

Type RM Length L Ch R = 1,2965,194,194,194
BEGIN DESCRIPTION:
Mapping XS ec1f707c
END DESCRIPTION:
XS GIS Cut Line= 3
      1674330.56      7017262.15      1674481.57      7017165.81
      1674706.05      7016978.17
#Sta/Elev= 30
  4820.2 1528.88  4855.8 1527.32  4861.4 1527.66  4870.7 1527.16  4876.6 1527.49
  4884.8 1526.64  4895.0 1526.60  4907.1 1526.11  4913.0 1526.41  4928.2 1525.08
  4949.4 1524.73  4970.6 1522.69  4979.7 1521.12  4985.8 1518.84  4989.7 1518.36
  4990.0 1517.86  4993.5 1517.86  4993.7 1518.36  4998.4 1519.32  5001.5 1519.32
  5014.8 1521.07  5035.6 1521.58  5042.9 1522.13  5072.1 1521.66  5078.6 1521.56
  5085.1 1522.07  5092.9 1521.59  5191.8 1522.64  5234.7 1522.60  5291.9 1523.97
#Mann=6,-1,0
  4820.2   0.035       0  4855.8    0.07       0  4895.0   0.035       0
  4989.7   0.035       0  4993.7   0.035       0  5072.1    0.07       0
Bank Sta=4989.7,4993.7
Exp/Cntr=0.3,0.1

Type RM Length L Ch R = 1,2771,546,546,546
BEGIN DESCRIPTION:
Mapping XS 65332468
END DESCRIPTION:
XS GIS Cut Line= 3
      1674363.24      7017424.96      1674602.63      7017289.02
      1674757.06      7017031.35
#Sta/Elev= 30
  4724.7 1523.71  4730.6 1524.05  4738.2 1523.55  4752.2 1523.63  4768.1 1522.41
  4789.7 1523.05  4805.6 1522.51  4841.7 1522.51  4848.8 1521.98  4870.4 1522.19
  4945.2 1521.24  4951.2 1520.50  4955.0 1518.01  4955.2 1517.51  4958.7 1517.51
  4959.0 1518.01  4967.1 1518.50  4972.8 1519.82  4979.7 1519.98  5010.7 1520.08
  5016.5 1519.62  5053.4 1519.01  5069.0 1519.70  5082.8 1519.69  5111.8 1519.01
  5127.3 1519.90  5185.5 1520.97  5212.9 1521.14  5275.3 1523.14  5300.4 1524.12
#Mann=5,-1,0
  4724.7   0.035       0  4955.0   0.035       0  4959.0   0.035       0
  5185.5    0.07       0  5275.3   0.035       0
Bank Sta=4955,4959
Exp/Cntr=0.3,0.1

Type RM Length L Ch R = 1,2225,335,335,335
BEGIN DESCRIPTION:
Mapping XS eca0e79d
END DESCRIPTION:
XS GIS Cut Line= 3
      1674332.21      7017441.42      1674703.27      7017468.55
      1674930.06      7017485.91
#Sta/Elev= 30
  4626.4 1524.00  4644.6 1523.96  4669.3 1523.59  4689.4 1522.47  4699.4 1521.62
  4739.5 1521.13  4779.6 1519.98  4789.9 1519.40  4866.4 1518.08  4899.9 1517.24
  4909.9 1516.52  4940.0 1516.80  4950.0 1515.99  4980.1 1515.48  4990.2 1515.07
  4996.8 1514.47  5010.2 1514.65  5018.2 1514.44  5018.5 1513.94  5022.0 1513.94
  5022.2 1514.44  5040.3 1515.28  5056.1 1516.66  5061.1 1516.58  5120.5 1518.85
  5140.6 1521.64  5150.7 1522.28  5186.8 1523.67  5191.8 1523.39  5225.9 1524.12
#Mann=6,-1,0
  4626.4    0.07       0  4644.6   0.035       0  4866.4    0.07       0
  5018.2    0.07       0  5022.2    0.07       0  5150.7   0.035       0
Bank Sta=5018.2,5022.2
Exp/Cntr=0.3,0.1

Type RM Length L Ch R = 1,1890,294,294,294
BEGIN DESCRIPTION:
Chimney Creek 1184 4.0
END DESCRIPTION:
XS GIS Cut Line= 3
      1674354.97      7017888.01      1674655.00      7017788.00
      1675004.97      7017438.03
#Sta/Elev= 30
  4684.2 1527.07  4715.9 1525.59  4736.9 1525.02  4758.0 1523.67  4789.6 1522.59
  4821.3 1520.29  4874.0 1518.50  4905.6 1515.98  4916.1 1515.77  4926.7 1515.13
  4937.2 1514.28  4958.3 1511.84  4977.1 1510.98  4987.9 1510.39  4988.2 1509.89
  4991.7 1509.89  4992.0 1510.39  5028.7 1510.75  5057.0 1514.03  5071.2 1514.54
  5117.9 1514.92  5136.4 1514.65  5170.2 1514.69  5184.3 1515.21  5240.9 1519.09
  5297.4 1520.11  5371.4 1522.66  5396.4 1523.84  5410.6 1523.84  5495.4 1525.81
#Mann=7,-1,0
  4684.2   0.035       0  4977.1    0.07       0  4987.9    0.07       0
  4992.0    0.07       0  5117.9   0.035       0  5136.4    0.07       0
  5371.4   0.035       0
Bank Sta=4987.9,4992
Exp/Cntr=0.3,0.1

Type RM Length L Ch R = 1,1596,314,314,314
BEGIN DESCRIPTION:
Chimney Creek 1184 3.0
END DESCRIPTION:
XS GIS Cut Line= 3
      1674625.46      7018222.47      1674847.35      7017979.97
      1675208.16      7017577.92
#Sta/Elev= 30
  4671.3 1528.79  4745.1 1525.85  4758.8 1525.78  4849.9 1520.99  4875.1 1519.86
  4886.4 1519.76  4914.8 1517.40  4943.2 1511.73  4957.4 1510.67  4964.1 1509.21
  4978.3 1508.45  4992.5 1508.70  5026.3 1507.64  5026.6 1507.14  5030.2 1507.14
  5030.4 1507.64  5042.6 1508.44  5049.3 1508.13  5063.5 1509.59  5070.2 1511.13
  5091.9 1511.99  5204.8 1513.29  5261.6 1515.48  5326.3 1517.03  5346.8 1518.14
  5381.9 1518.83  5467.1 1522.71  5524.3 1524.35  5538.7 1524.77  5540.2 1524.77
#Mann=8,-1,0
  4671.3   0.035       0  4849.9    0.07       0  4875.1   0.035       0
  5026.3   0.035       0  5030.4   0.035       0  5326.3    0.07       0
  5524.3   0.035       0  5538.7    0.07       0
Bank Sta=5026.3,5030.4
Exp/Cntr=0.3,0.1

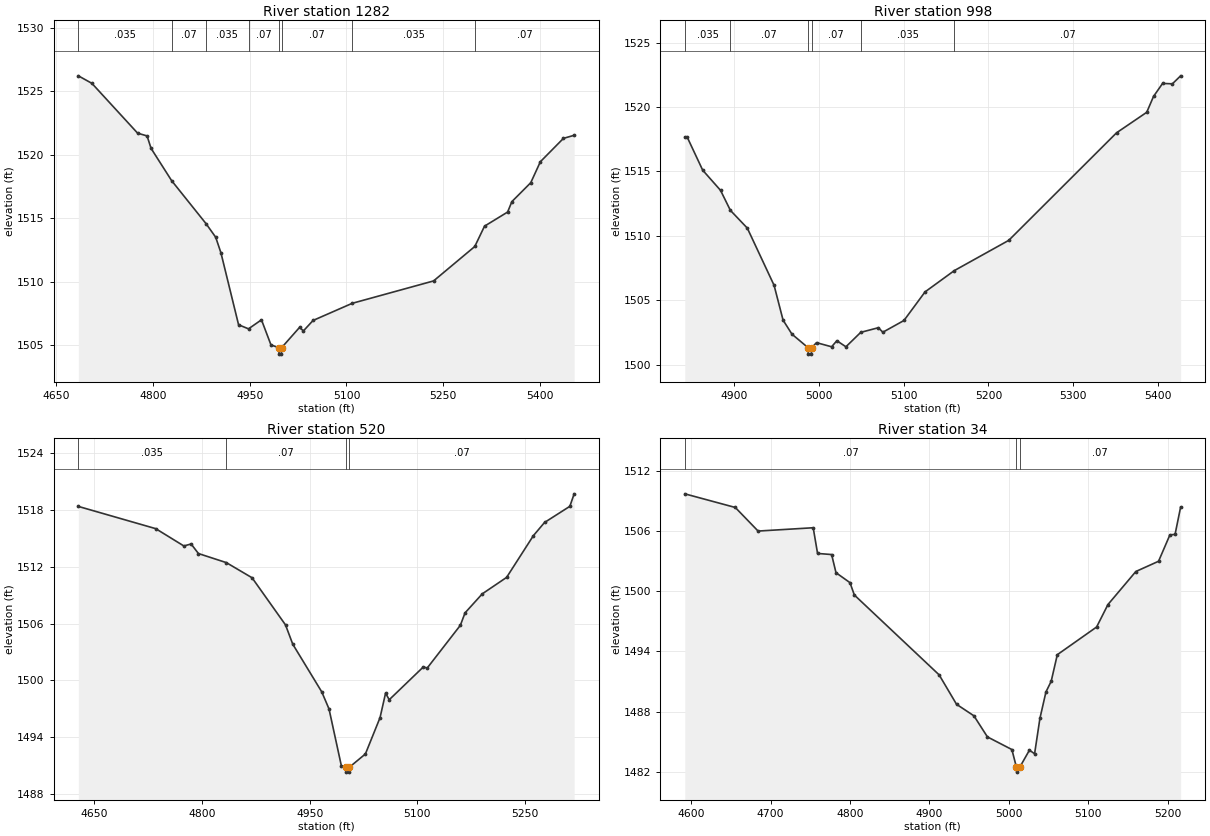
Type RM Length L Ch R = 1,1282,284,284,284
BEGIN DESCRIPTION:
Mapping XS 22402e00
END DESCRIPTION:
XS GIS Cut Line= 3
      1674914.70      7018395.98      1675100.92      7018143.34
      1675358.72      7017768.36
#Sta/Elev= 30
  4684.2 1526.22  4705.2 1525.63  4776.1 1521.71  4790.8 1521.49  4797.0 1520.51
  4828.9 1517.97  4882.2 1514.59  4897.2 1513.52  4905.3 1512.30  4932.7 1506.63
  4948.1 1506.31  4968.2 1507.02  4982.9 1505.05  4995.2 1504.82  4995.5 1504.32
  4999.1 1504.32  4999.3 1504.82  5027.2 1506.42  5033.3 1506.15  5048.2 1506.97
  5109.0 1508.32  5235.1 1510.08  5299.0 1512.79  5314.1 1514.39  5349.9 1515.50
  5356.5 1516.32  5385.8 1517.81  5400.7 1519.46  5436.5 1521.30  5453.1 1521.54
#Mann=8,-1,0
  4684.2   0.035       0  4828.9    0.07       0  4882.2   0.035       0
  4948.1    0.07       0  4995.2    0.07       0  4999.3    0.07       0
  5109.0   0.035       0  5299.0    0.07       0
Bank Sta=4995.2,4999.3
Exp/Cntr=0.3,0.1

Type RM Length L Ch R = 1,998,478,478,478
BEGIN DESCRIPTION:
Chimney Creek 1184 2.0
END DESCRIPTION:
XS GIS Cut Line= 3
      1675304.99      7018388.03      1675355.00      7018238.00
      1675504.98      7017838.04
#Sta/Elev= 30
  4841.5 1517.68  4844.2 1517.68  4862.6 1515.10  4883.7 1513.53  4895.3 1511.98
  4915.3 1510.60  4946.9 1506.16  4957.5 1503.46  4968.0 1502.37  4987.0 1501.32
  4987.3 1500.82  4990.9 1500.82  4991.2 1501.32  4997.0 1501.71  5014.8 1501.39
  5021.0 1501.86  5031.7 1501.39  5049.2 1502.51  5070.0 1502.87  5075.3 1502.52
  5100.2 1503.43  5125.1 1505.65  5159.6 1507.30  5223.9 1509.65  5351.2 1518.00
  5386.8 1519.59  5394.8 1520.82  5405.5 1521.83  5417.1 1521.80  5426.8 1522.42
#Mann=6,-1,0
  4841.5   0.035       0  4895.3    0.07       0  4987.0    0.07       0
  4991.2    0.07       0  5049.2   0.035       0  5159.6    0.07       0
Bank Sta=4987,4991.2
Exp/Cntr=0.3,0.1

Type RM Length L Ch R = 1,520,486,486,486
BEGIN DESCRIPTION:
Mapping XS 7669a762
END DESCRIPTION:
XS GIS Cut Line= 3
      1675855.17      7018603.46      1675801.36      7018238.91
      1675742.50      7017922.13
#Sta/Elev= 30
  4627.7 1518.38  4735.5 1516.03  4774.7 1514.20  4784.8 1514.41  4795.0 1513.40
  4833.9 1512.44  4869.7 1510.84  4916.3 1505.86  4926.4 1503.82  4966.8 1498.78
  4976.9 1496.98  4994.1 1490.97  5000.8 1490.80  5001.1 1490.30  5004.8 1490.30
  5005.0 1490.80  5027.6 1492.22  5048.0 1496.06  5055.7 1498.65  5060.8 1497.95
  5108.5 1501.43  5113.6 1501.29  5159.9 1505.82  5166.4 1507.13  5190.4 1509.14
  5224.3 1510.88  5261.6 1515.29  5277.1 1516.68  5312.4 1518.39  5318.4 1519.71
#Mann=4,-1,0
  4627.7   0.035       0  4833.9    0.07       0  5000.8    0.07       0
  5005.0    0.07       0
Bank Sta=5000.8,5005
Exp/Cntr=0.3,0.1

Type RM Length L Ch R = 1,34,0,0,0
BEGIN DESCRIPTION:
Chimney Creek 1184 1.0
END DESCRIPTION:
XS GIS Cut Line= 3
      1676103.45      7018560.07      1676270.86      7018188.00
      1676131.57      7018022.39
#Sta/Elev= 30
  4592.0 1509.71  4655.6 1508.35  4684.3 1506.00  4753.7 1506.33  4759.2 1503.77
  4776.9 1503.66  4782.4 1501.85  4800.0 1500.86  4805.5 1499.63  4912.3 1491.67
  4934.2 1488.74  4956.1 1487.59  4973.1 1485.49  5003.9 1484.23  5009.6 1482.48
  5009.9 1481.98  5013.9 1482.48  5026.0 1484.17  5032.5 1483.81  5039.2 1487.33
  5046.8 1489.97  5053.4 1491.03  5061.1 1493.68  5110.6 1496.44  5124.9 1498.68
  5160.0 1501.97  5188.6 1502.99  5202.9 1505.62  5209.4 1505.67  5216.4 1508.39
#Mann=3,-1,0
  4592.0    0.07       0  5009.6    0.07       0  5013.9    0.07       0
Bank Sta=5009.6,5013.9
Exp/Cntr=0.3,0.1

Chan Stop Cuts=-1