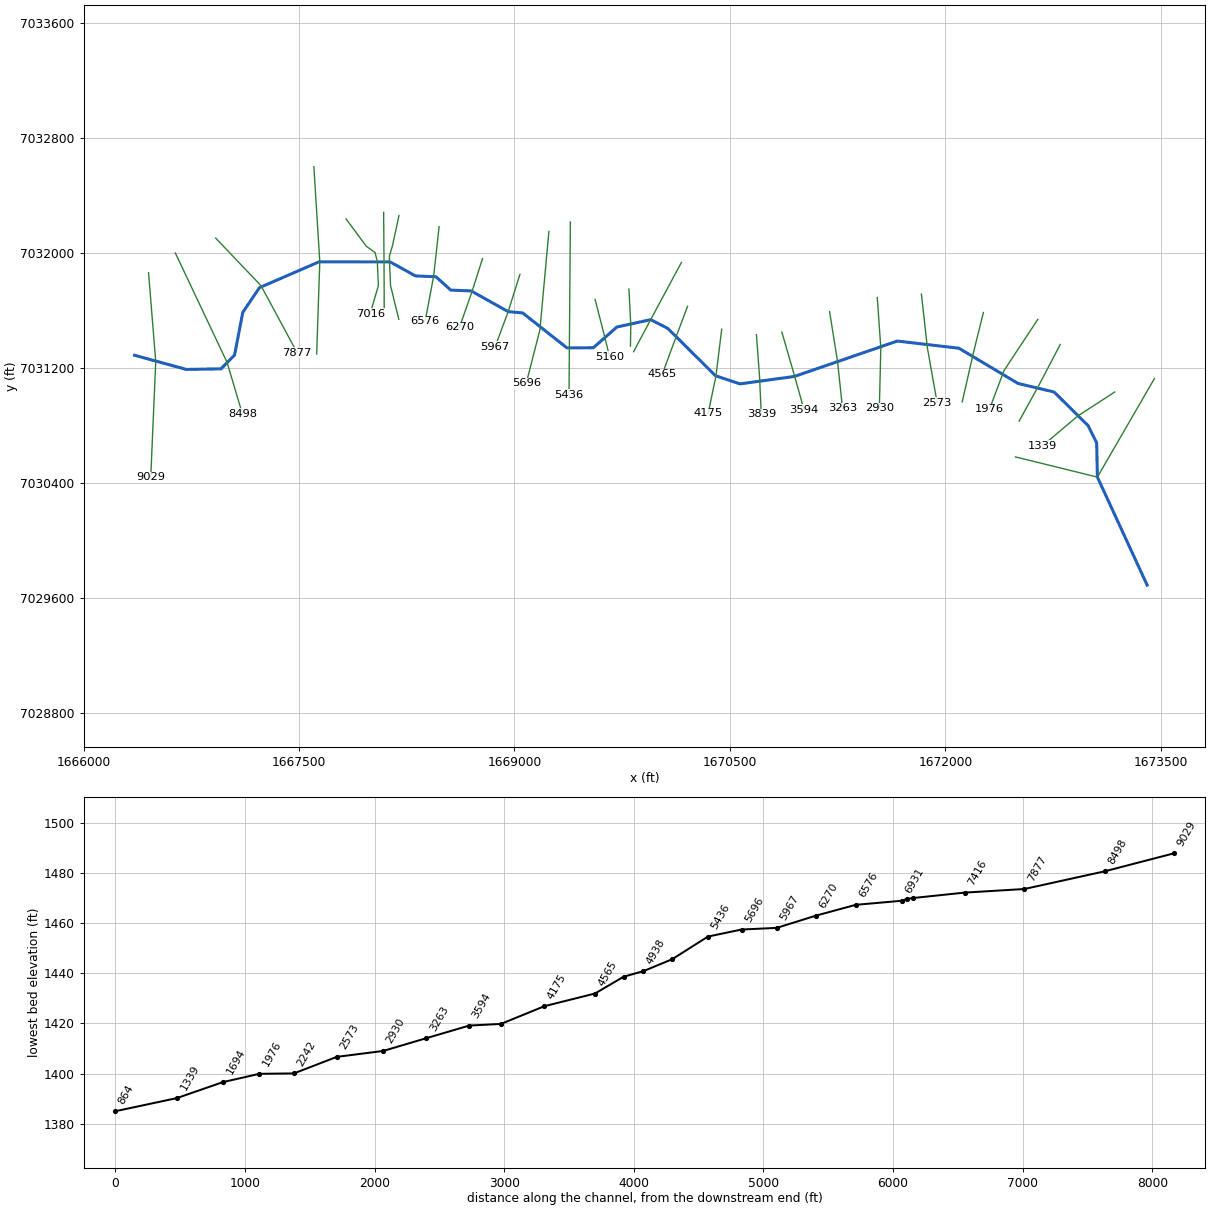
--- Chimney Creek 1185.prj (project) ---

Proj Title=Chimney Creek 1185 Base Level Engineering
Current Plan=p01
Default Exp/Contr=0.3,0.1
English Units
Geom File=g01
Flow File=f01
Plan File=p01
BEGIN DESCRIPTION:
Chimney Creek 1185
END DESCRIPTION:

--- Chimney Creek 1185.p01 (plan) ---

Plan Title=Multiple Run
Short Identifier=Multiple
Geom File=g01
Flow File=f01
Subcritical Flow
K Sum by GR= 0
Std Step Tol= 0.01
Critical Tol= 0.01
Num of Std Step Trials= 20
Max Error Tol= 0.3
Flow Tol Ratio= 0.001
Split Flow NTrial= 30
Split Flow Tol= 0.02
Split Flow Ratio= 0.02
Log Output Level= 0
Friction Slope Method= 1
Unsteady Friction Slope Method= 2
Unsteady Bridges Friction Slope Method= 1
Parabolic Critical Depth
Global Vel Dist=  1 , 1 , 1
Global Log Level= 0
CheckData=True
Encroach Param= -1, 0, 0, 0
BEGIN DESCRIPTION:
Multiple Run
END DESCRIPTION:

--- Chimney Creek 1185.f01 (steady flow) ---

Flow Title=Multiple
Number of Profiles=7
Profile Names=10-year,25-year,50-year,1pct_min,100-year,1pct_plu,500-year
River Rch & RM= Chimney Creek 11,Reach-1,9029
     483     698     884     558    1113    2220    1784
River Rch & RM= Chimney Creek 11,Reach-1,4565
     578     840    1067     675    1347    2687    2171
Boundary for River Rch & Prof#=Chimney Creek 11,Reach-1,1
Up Type=0
Dn Type=3
Dn Slope=0.005
Boundary for River Rch & Prof#=Chimney Creek 11,Reach-1,2
Up Type=0
Dn Type=3
Dn Slope=0.005
Boundary for River Rch & Prof#=Chimney Creek 11,Reach-1,3
Up Type=0
Dn Type=3
Dn Slope=0.005
Boundary for River Rch & Prof#=Chimney Creek 11,Reach-1,4
Up Type=0
Dn Type=3
Dn Slope=0.005
Boundary for River Rch & Prof#=Chimney Creek 11,Reach-1,5
Up Type=0
Dn Type=3
Dn Slope=0.005
Boundary for River Rch & Prof#=Chimney Creek 11,Reach-1,6
Up Type=0
Dn Type=3
Dn Slope=0.005
Boundary for River Rch & Prof#=Chimney Creek 11,Reach-1,7
Up Type=0
Dn Type=3
Dn Slope=0.005

--- Chimney Creek 1185.g01 (geometry) ---

Geom Title=Existing Conditions

River Reach=Chimney Creek 11,Reach-1
Reach XY= 30
      1666355.00      7031288.00      1666715.50      7031189.22
      1666957.47      7031193.45      1667051.46      7031289.46
      1667108.62      7031586.50      1667224.63      7031758.48
      1667639.82      7031938.44      1668134.71      7031937.71
      1668310.94      7031840.27      1668453.53      7031834.44
      1668556.47      7031741.56      1668699.06      7031735.73
      1668956.50      7031591.63      1669057.43      7031582.48
      1669365.48      7031339.19      1669549.15      7031340.06
      1669713.48      7031484.51      1669949.03      7031535.86
      1670068.22      7031474.38      1670398.83      7031145.86
      1670568.97      7031088.55      1670949.06      7031140.26
      1671665.51      7031386.79      1672094.52      7031336.81
      1672506.47      7031091.56      1672757.30      7031032.17
      1672994.24      7030797.68      1673053.80      7030677.50
      1673058.75      7030439.55      1673405.00      7029688.00

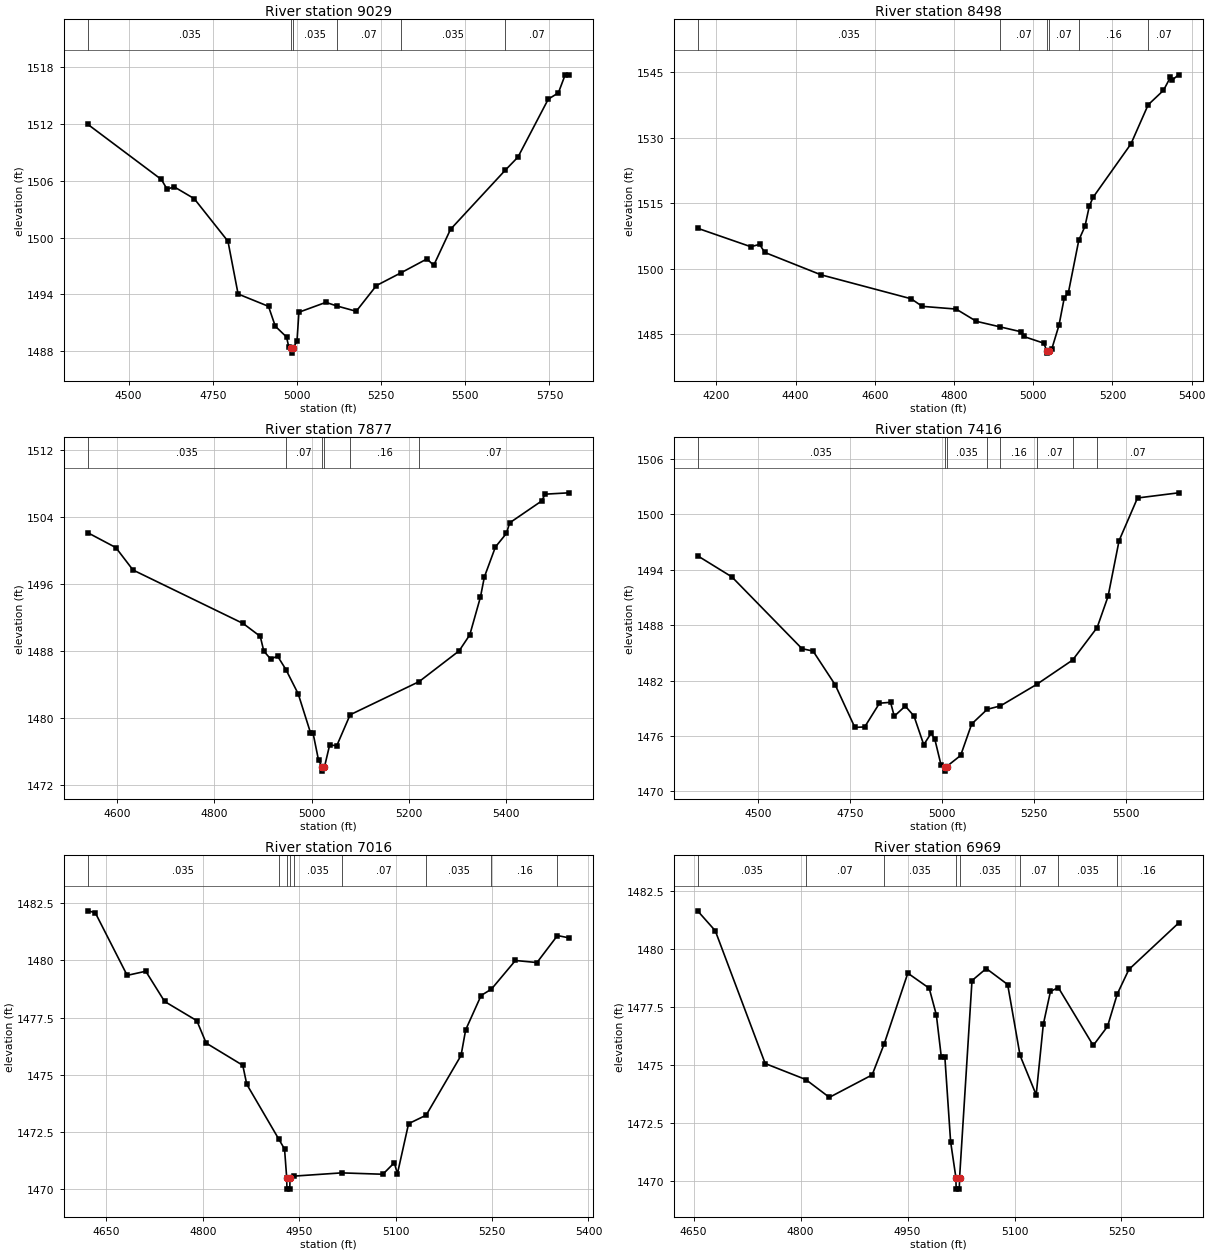
Type RM Length L Ch R = 1,9029,531,531,531
BEGIN DESCRIPTION:
Chimney Creek 1185 19.0
END DESCRIPTION:
XS GIS Cut Line= 3
      1666452.58      7031862.89      1666502.65      7031243.71
      1666467.77      7030437.17
#Sta/Elev= 30
  4378.8 1511.93  4597.2 1506.12  4614.5 1505.08  4634.5 1505.36  4694.7 1504.10
  4795.0 1499.61  4825.1 1494.05  4915.4 1492.75  4935.5 1490.66  4968.9 1489.52
  4975.6 1488.48  4983.6 1488.32  4983.9 1487.82  4987.7 1488.32  5000.0 1489.06
  5005.7 1492.13  5085.8 1493.17  5118.5 1492.79  5175.9 1492.23  5235.9 1494.94
  5307.6 1496.26  5386.1 1497.75  5406.1 1497.07  5456.1 1500.87  5618.1 1507.08
  5656.3 1508.48  5746.4 1514.59  5776.4 1515.25  5796.5 1517.15  5807.3 1517.15
#Mann=6,-1,0
  4378.8   0.035       0  4983.6   0.035       0  4987.7   0.035       0
  5118.5    0.07       0  5307.6   0.035       0  5618.1    0.07       0
Bank Sta=4983.6,4987.7
Exp/Cntr=0.3,0.1

Type RM Length L Ch R = 1,8498,621,621,621
BEGIN DESCRIPTION:
Mapping XS 2a6f4e8e
END DESCRIPTION:
XS GIS Cut Line= 3
      1666639.21      7031999.65      1666999.45      7031237.93
      1667105.32      7030881.43
#Sta/Elev= 30
  4152.4 1509.26  4287.0 1505.03  4309.1 1505.58  4321.8 1503.74  4464.0 1498.61
  4691.5 1493.13  4719.8 1491.39  4805.3 1490.77  4856.3 1487.97  4917.0 1486.68
  4970.1 1485.56  4975.6 1484.51  5026.2 1482.98  5034.8 1481.19  5035.1 1480.69
  5039.1 1481.19  5047.1 1481.71  5065.0 1487.06  5078.4 1493.35  5088.8 1494.54
  5115.1 1506.54  5130.6 1509.68  5141.8 1514.39  5151.4 1516.37  5246.7 1528.55
  5290.2 1537.50  5328.8 1540.80  5346.3 1543.78  5351.5 1543.20  5366.9 1544.36
#Mann=6,-1,0
  4152.4   0.035       0  4917.0    0.07       0  5034.8    0.07       0
  5039.1    0.07       0  5115.1    0.16       0  5290.2    0.07       0
Bank Sta=5034.8,5039.1
Exp/Cntr=0.3,0.1

Type RM Length L Ch R = 1,7877,461,461,461
BEGIN DESCRIPTION:
Mapping XS 54e922a7
END DESCRIPTION:
XS GIS Cut Line= 3
      1666919.60      7032103.91      1667235.56      7031772.33
      1667487.32      7031305.28
#Sta/Elev= 30
  4539.7 1502.10  4597.2 1500.33  4632.5 1497.65  4858.9 1491.26  4894.1 1489.72
  4901.4 1487.96  4915.5 1487.01  4929.7 1487.36  4946.9 1485.75  4972.2 1482.84
  4997.3 1478.22  5002.4 1478.22  5014.0 1474.90  5021.7 1474.12  5022.0 1473.62
  5026.1 1474.12  5036.7 1476.73  5051.5 1476.67  5078.8 1480.35  5220.5 1484.31
  5302.9 1487.99  5324.8 1489.90  5346.7 1494.41  5354.8 1496.82  5377.5 1500.40
  5400.2 1502.03  5406.7 1503.28  5472.4 1505.89  5479.8 1506.71  5528.3 1506.87
#Mann=6,-1,0
  4539.7   0.035       0  4946.9    0.07       0  5021.7    0.07       0
  5026.1    0.07       0  5078.8    0.16       0  5220.5    0.07       0
Bank Sta=5021.7,5026.1
Exp/Cntr=0.3,0.1

Type RM Length L Ch R = 1,7416,400,400,400
BEGIN DESCRIPTION:
Mapping XS 10ea1230
END DESCRIPTION:
XS GIS Cut Line= 3
      1667603.56      7032600.96      1667644.79      7031939.05
      1667623.09      7031296.71
#Sta/Elev= 30
  4336.2 1495.52  4429.3 1493.23  4619.7 1485.45  4649.8 1485.19  4709.9 1481.53
  4763.2 1476.92  4790.0 1476.97  4830.1 1479.54  4860.2 1479.64  4870.2 1478.13
  4900.2 1479.23  4923.8 1478.15  4950.3 1475.04  4970.4 1476.29  4980.4 1475.63
  4997.4 1472.82  5008.2 1472.68  5008.5 1472.18  5012.6 1472.68  5050.5 1473.88
  5080.5 1477.29  5122.7 1478.88  5158.6 1479.25  5256.6 1481.57  5354.6 1484.22
  5421.1 1487.74  5450.7 1491.11  5480.7 1497.16  5530.7 1501.78  5642.1 1502.34
#Mann=8,-1,0
  4336.2   0.035       0  5008.2   0.035       0  5012.6   0.035       0
  5122.7    0.07       0  5158.6    0.16       0  5256.6    0.07       0
  5354.6    0.16       0  5421.1    0.07       0
Bank Sta=5008.2,5012.6
Exp/Cntr=0.3,0.1

Type RM Length L Ch R = 1,7016,47,47,47
BEGIN DESCRIPTION:
Mapping XS 3dfa92a1
END DESCRIPTION:
XS GIS Cut Line= 6
      1667827.73      7032237.24      1667968.36      7032047.13
      1668029.56      7032002.86      1668045.18      7031940.36
      1668053.00      7031773.69      1667995.70      7031577.05
#Sta/Elev= 30
  4621.3 1482.17  4632.8 1482.09  4682.5 1479.35  4711.4 1479.53  4740.7 1478.21
  4790.8 1477.37  4805.4 1476.39  4862.3 1475.42  4868.5 1474.59  4918.6 1472.18
  4927.3 1471.76  4930.6 1470.51  4931.0 1470.01  4935.4 1470.01  4935.8 1470.51
  4942.6 1470.58  5016.0 1470.72  5080.2 1470.66  5097.9 1471.16  5102.9 1470.69
  5120.2 1472.87  5147.5 1473.24  5201.8 1475.85  5209.0 1476.97  5233.0 1478.47
  5249.1 1478.75  5286.4 1480.00  5319.9 1479.91  5351.8 1481.09  5369.4 1480.99
#Mann=9,-1,0
  4621.3   0.035       0  4918.6    0.07       0  4930.6   0.035       0
  4935.8    0.07       0  4942.6   0.035       0  5016.0    0.07       0
  5147.5   0.035       0  5249.1    0.16       0  5351.8   0.035       0
Bank Sta=4930.6,4935.8
Exp/Cntr=0.3,0.1

Type RM Length L Ch R = 1,6969,38,38,38
BEGIN DESCRIPTION:
Mapping XS 4749de82
END DESCRIPTION:
XS GIS Cut Line= 3
      1668089.45      7032282.76      1668092.06      7031939.05
      1668093.36      7031608.37
#Sta/Elev= 30
  4655.6 1481.64  4680.4 1480.78  4750.4 1475.05  4807.3 1474.36  4840.4 1473.59
  4900.4 1474.56  4917.4 1475.91  4950.4 1478.95  4980.4 1478.30  4990.4 1477.15
  4997.3 1475.35  5002.3 1475.35  5010.4 1471.68  5017.8 1470.13  5018.2 1469.63
  5022.6 1469.63  5023.0 1470.13  5040.4 1478.63  5060.4 1479.15  5090.4 1478.46
  5107.8 1475.40  5130.4 1473.70  5140.4 1476.74  5150.4 1478.16  5161.4 1478.33
  5210.4 1475.83  5230.4 1476.65  5244.1 1478.05  5260.4 1479.11  5330.0 1481.11
#Mann=8,-1,0
  4655.6   0.035       0  4807.3    0.07       0  4917.4   0.035       0
  5017.8   0.035       0  5023.0   0.035       0  5107.8    0.07       0
  5161.4   0.035       0  5244.1    0.16       0
Bank Sta=5017.8,5023
Exp/Cntr=0.3,0.1

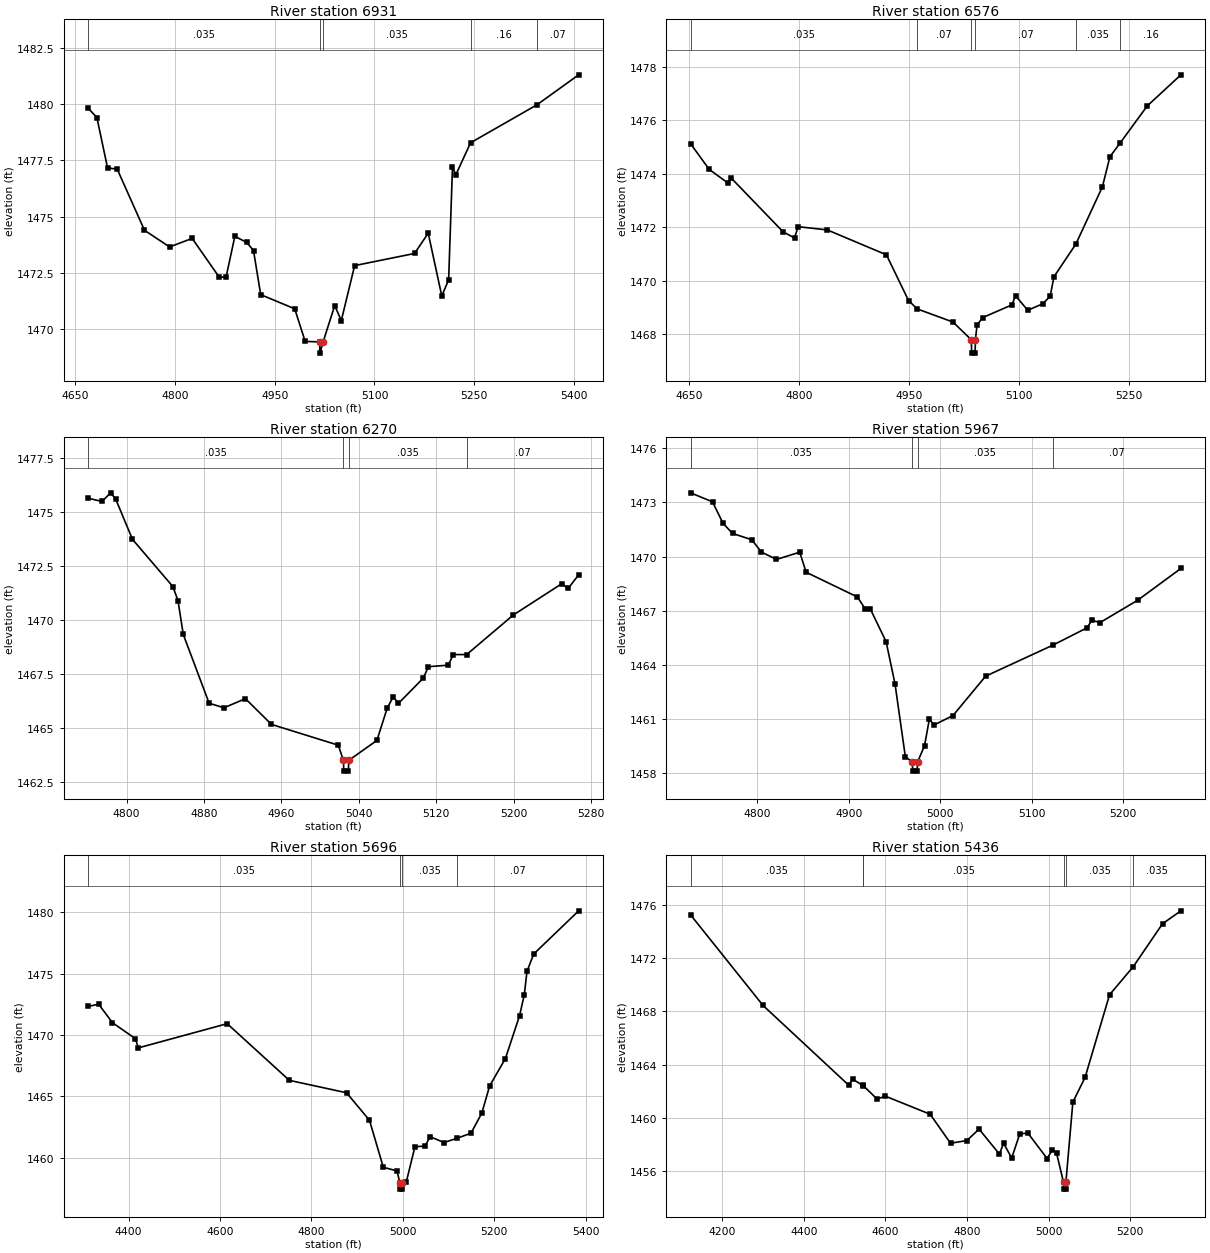
Type RM Length L Ch R = 1,6931,355,355,355
BEGIN DESCRIPTION:
Mapping XS 93aab8cf
END DESCRIPTION:
XS GIS Cut Line= 6
      1668196.22      7032260.64      1668150.65      7032049.73
      1668129.82      7031979.42      1668129.82      7031941.66
      1668137.63      7031772.39      1668194.92      7031538.01
#Sta/Elev= 30
  4669.6 1479.81  4682.5 1479.40  4698.5 1477.17  4713.2 1477.10  4754.1 1474.39
  4791.9 1473.65  4825.8 1474.03  4866.7 1472.30  4876.9 1472.32  4890.0 1474.12
  4908.0 1473.85  4918.1 1473.49  4928.9 1471.53  4980.1 1470.90  4995.8 1469.45
  5017.6 1469.43  5018.0 1468.93  5022.8 1469.43  5040.2 1471.04  5050.2 1470.38
  5070.2 1472.82  5160.3 1473.36  5180.9 1474.26  5201.3 1471.47  5211.6 1472.19
  5217.4 1477.20  5222.5 1476.86  5244.6 1478.28  5344.6 1479.97  5407.2 1481.30
#Mann=5,-1,0
  4669.6   0.035       0  5017.6   0.035       0  5022.8   0.035       0
  5244.6    0.16       0  5344.6    0.07       0
Bank Sta=5017.6,5022.8
Exp/Cntr=0.3,0.1

Type RM Length L Ch R = 1,6576,306,306,306
BEGIN DESCRIPTION:
Mapping XS c8d9dd7e
END DESCRIPTION:
XS GIS Cut Line= 3
      1668475.52      7032183.21      1668437.76      7031839.44
      1668377.86      7031523.00
#Sta/Elev= 30
  4652.5 1475.12  4677.9 1474.16  4703.0 1473.66  4708.1 1473.83  4778.5 1471.83
  4794.1 1471.60  4799.1 1472.02  4838.8 1471.90  4919.3 1470.97  4949.5 1469.26
  4961.3 1468.95  5010.0 1468.46  5034.9 1467.80  5035.4 1467.30  5040.1 1467.30
  5040.5 1467.80  5042.8 1468.36  5050.7 1468.63  5090.1 1469.10  5095.2 1469.44
  5111.8 1468.90  5132.1 1469.14  5142.3 1469.42  5147.5 1470.15  5177.5 1471.38
  5213.5 1473.51  5223.7 1474.63  5237.5 1475.14  5274.6 1476.53  5320.4 1477.69
#Mann=6,-1,0
  4652.5   0.035       0  4961.3    0.07       0  5034.9    0.07       0
  5040.5    0.07       0  5177.5   0.035       0  5237.5    0.16       0
Bank Sta=5034.9,5040.5
Exp/Cntr=0.3,0.1

Type RM Length L Ch R = 1,6270,303,303,303
BEGIN DESCRIPTION:
Mapping XS 8ad07be6
END DESCRIPTION:
XS GIS Cut Line= 3
      1668778.09      7031961.45      1668705.38      7031733.54
      1668616.99      7031481.30
#Sta/Elev= 30
  4760.5 1475.63  4774.6 1475.48  4783.5 1475.88  4788.7 1475.60  4806.1 1473.73
  4847.9 1471.54  4853.1 1470.90  4858.6 1469.33  4885.3 1466.15  4900.6 1465.94
  4922.8 1466.36  4949.7 1465.17  5018.7 1464.21  5024.0 1463.51  5024.4 1463.01
  5029.1 1463.01  5029.6 1463.51  5058.6 1464.43  5069.2 1465.92  5075.5 1466.45
  5080.8 1466.14  5106.5 1467.31  5111.8 1467.84  5132.2 1467.91  5137.5 1468.40
  5151.3 1468.40  5199.5 1470.23  5249.3 1471.67  5256.2 1471.46  5267.0 1472.09
#Mann=4,-1,0
  4760.5   0.035       0  5024.0   0.035       0  5029.6   0.035       0
  5151.3    0.07       0
Bank Sta=5024,5029.6
Exp/Cntr=0.3,0.1

Type RM Length L Ch R = 1,5967,271,271,271
BEGIN DESCRIPTION:
Mapping XS 74aef088
END DESCRIPTION:
XS GIS Cut Line= 3
      1669038.49      7031851.82      1668956.03      7031590.31
      1668864.89      7031345.11
#Sta/Elev= 30
  4727.2 1473.53  4751.2 1473.03  4762.7 1471.84  4773.1 1471.28  4794.1 1470.93
  4804.6 1470.25  4821.1 1469.84  4846.5 1470.24  4853.5 1469.13  4909.5 1467.76
  4918.2 1467.09  4923.4 1467.12  4940.9 1465.28  4950.6 1462.95  4961.9 1458.91
  4969.5 1458.61  4970.0 1458.11  4974.8 1458.11  4975.2 1458.61  4982.9 1459.52
  4988.1 1460.98  4993.4 1460.67  5014.0 1461.19  5049.6 1463.37  5123.1 1465.09
  5160.4 1466.05  5165.7 1466.47  5174.6 1466.34  5215.8 1467.58  5263.0 1469.34
#Mann=4,-1,0
  4727.2   0.035       0  4969.5   0.035       0  4975.2   0.035       0
  5123.1    0.07       0
Bank Sta=4969.5,4975.2
Exp/Cntr=0.3,0.1

Type RM Length L Ch R = 1,5696,260,260,260
BEGIN DESCRIPTION:
Mapping XS 9b3bd587
END DESCRIPTION:
XS GIS Cut Line= 3
      1669240.09      7032150.58      1669177.38      7031465.10
      1669082.18      7031092.72
#Sta/Elev= 30
  4311.8 1472.33  4334.5 1472.50  4364.6 1471.00  4414.8 1469.70  4421.2 1468.95
  4615.6 1470.92  4751.5 1466.31  4876.7 1465.30  4926.9 1463.06  4957.1 1459.24
  4987.2 1458.94  4993.3 1457.96  4993.8 1457.46  4998.6 1457.46  4999.0 1457.96
  5007.5 1458.06  5026.4 1460.92  5048.8 1460.95  5059.1 1461.73  5090.0 1461.25
  5119.4 1461.61  5148.9 1462.01  5172.6 1463.64  5189.8 1465.86  5224.2 1468.08
  5255.2 1471.57  5265.5 1473.26  5271.4 1475.17  5286.2 1476.59  5384.5 1480.10
#Mann=4,-1,0
  4311.8   0.035       0  4993.3   0.035       0  4999.0   0.035       0
  5119.4    0.07       0
Bank Sta=4993.3,4999
Exp/Cntr=0.3,0.1

Type RM Length L Ch R = 1,5436,276,276,276
BEGIN DESCRIPTION:
Mapping XS 60837c54
END DESCRIPTION:
XS GIS Cut Line= 3
      1669389.39      7032215.70      1669382.46      7031339.23
      1669380.00      7031013.03
#Sta/Elev= 30
  4122.0 1475.26  4299.7 1468.45  4509.7 1462.46  4519.7 1462.90  4543.9 1462.45
  4546.1 1462.40  4579.7 1461.41  4599.7 1461.63  4709.7 1460.27  4759.7 1458.09
  4799.7 1458.29  4829.7 1459.15  4879.7 1457.27  4889.7 1458.09  4909.7 1456.98
  4929.7 1458.81  4949.7 1458.84  4996.6 1456.94  5009.7 1457.60  5019.7 1457.35
  5036.9 1455.14  5037.3 1454.64  5042.1 1454.64  5042.6 1455.14  5059.7 1461.18
  5089.7 1463.04  5149.7 1469.25  5207.8 1471.36  5279.7 1474.59  5324.7 1475.56
#Mann=6,-1,0
  4122.0   0.035       0  4543.9    0.07       0  4546.1   0.035       0
  5036.9   0.035       0  5042.6   0.035       0  5207.8   0.035       0
Bank Sta=5036.9,5042.6
Exp/Cntr=0.3,0.1

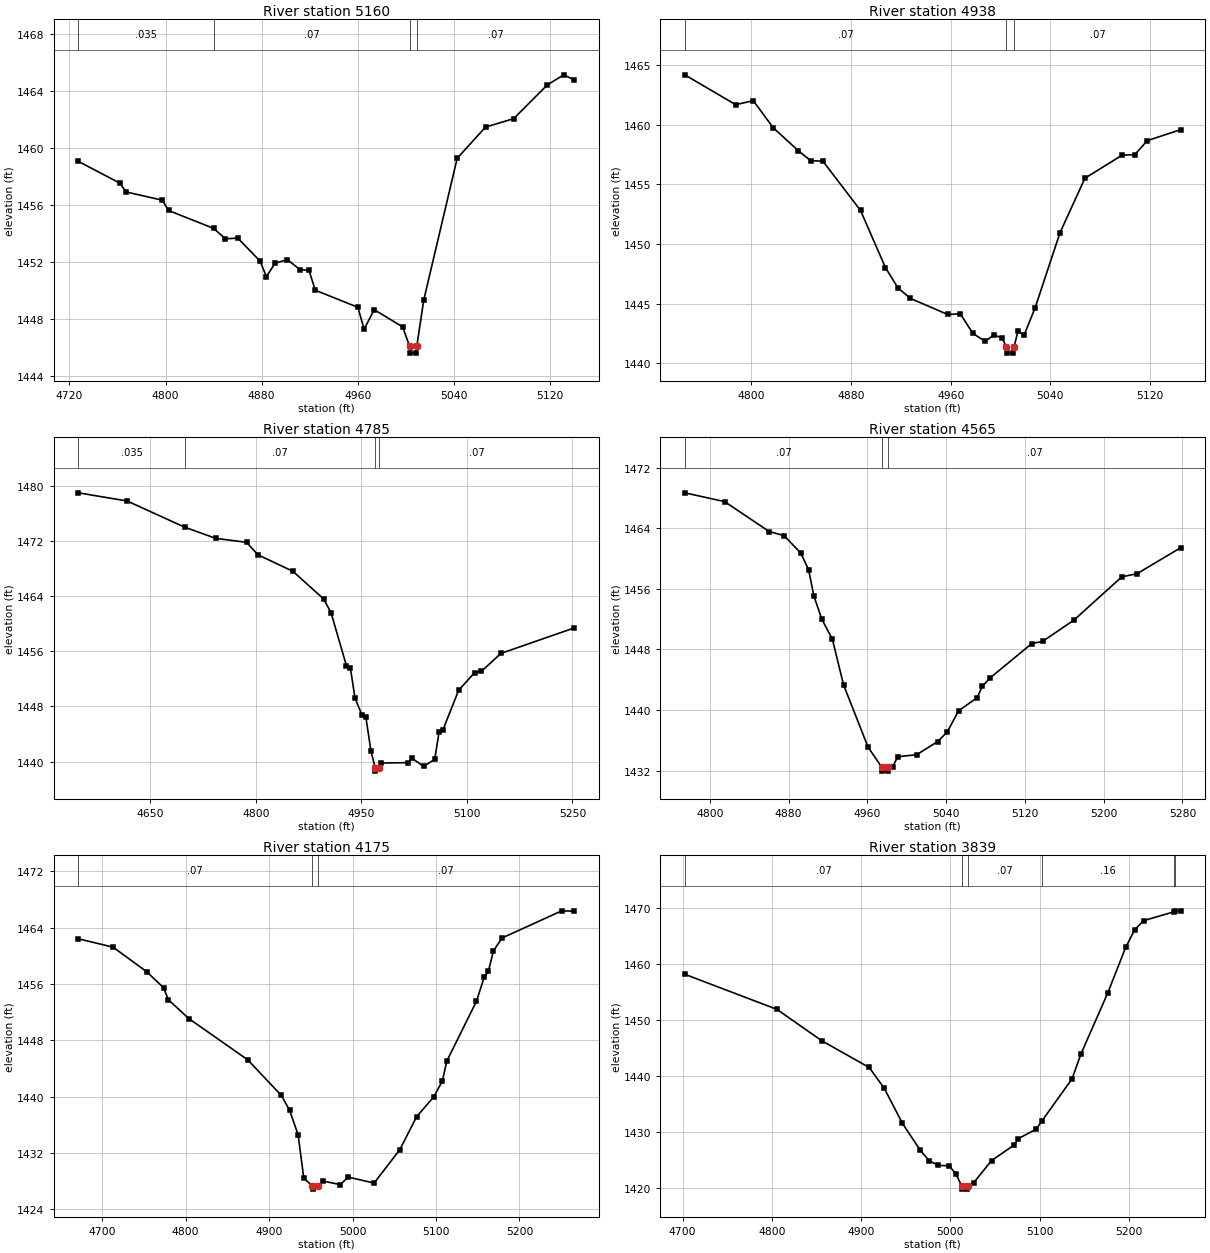
Type RM Length L Ch R = 1,5160,222,222,222
BEGIN DESCRIPTION:
Mapping XS 2380df42
END DESCRIPTION:
XS GIS Cut Line= 3
      1669561.51      7031676.64      1669628.77      7031415.18
      1669662.41      7031276.27
#Sta/Elev= 30
  4727.4 1459.08  4761.8 1457.56  4767.3 1456.93  4797.4 1456.35  4802.5 1455.63
  4840.1 1454.37  4849.9 1453.64  4860.2 1453.69  4878.8 1452.07  4884.0 1450.98
  4891.2 1451.92  4901.5 1452.18  4911.9 1451.48  4919.5 1451.42  4924.7 1450.03
  4960.2 1448.83  4965.4 1447.29  4973.8 1448.66  4997.4 1447.46  5003.2 1446.11
  5003.7 1445.61  5008.8 1445.61  5009.3 1446.11  5015.0 1449.32  5042.9 1459.30
  5066.5 1461.49  5089.9 1462.08  5117.9 1464.45  5131.7 1465.16  5140.3 1464.80
#Mann=4,-1,0
  4727.4   0.035       0  4840.1    0.07       0  5003.2    0.07       0
  5009.3    0.07       0
Bank Sta=5003.2,5009.3
Exp/Cntr=0.3,0.1

Type RM Length L Ch R = 1,4938,153,153,153
BEGIN DESCRIPTION:
Mapping XS c3c5f41d
END DESCRIPTION:
XS GIS Cut Line= 3
      1669797.23      7031748.77      1669810.25      7031494.46
      1669807.67      7031351.23
#Sta/Elev= 30
  4746.6 1464.19  4787.4 1461.69  4801.6 1462.02  4817.5 1459.76  4837.5 1457.84
  4847.5 1457.00  4857.5 1456.94  4887.6 1452.82  4907.6 1448.03  4917.6 1446.33
  4927.6 1445.44  4957.6 1444.09  4967.7 1444.15  4977.7 1442.51  4987.7 1441.83
  4994.5 1442.37  5001.2 1442.13  5004.7 1441.35  5005.2 1440.85  5010.3 1440.85
  5010.8 1441.35  5013.9 1442.68  5018.9 1442.37  5027.7 1444.64  5047.7 1450.95
  5067.7 1455.52  5097.7 1457.46  5107.7 1457.49  5117.7 1458.67  5144.5 1459.59
#Mann=3,-1,0
  4746.6    0.07       0  5004.7    0.07       0  5010.8    0.07       0
Bank Sta=5004.7,5010.8
Exp/Cntr=0.3,0.1

Type RM Length L Ch R = 1,4785,220,220,220
BEGIN DESCRIPTION:
Mapping XS 4e9d6e1f
END DESCRIPTION:
XS GIS Cut Line= 3
      1670162.82      7031934.42      1669949.14      7031537.00
      1669830.02      7031313.03
#Sta/Elev= 30
  4547.6 1479.01  4617.1 1477.82  4698.7 1474.03  4742.9 1472.40  4786.7 1471.83
  4803.0 1470.01  4852.5 1467.63  4896.3 1463.61  4906.9 1461.60  4928.8 1453.90
  4934.4 1453.56  4940.9 1449.24  4950.7 1446.79  4956.4 1446.43  4963.6 1441.56
  4969.5 1439.12  4970.0 1438.62  4975.7 1439.12  4978.3 1439.80  5016.5 1439.85
  5022.1 1440.48  5038.5 1439.31  5054.3 1440.33  5060.4 1444.28  5066.1 1444.65
  5088.3 1450.36  5111.0 1452.92  5120.7 1453.11  5148.3 1455.70  5252.5 1459.40
#Mann=4,-1,0
  4547.6   0.035       0  4698.7    0.07       0  4969.5    0.07       0
  4975.7    0.07       0
Bank Sta=4969.5,4975.7
Exp/Cntr=0.3,0.1

Type RM Length L Ch R = 1,4565,390,390,390
BEGIN DESCRIPTION:
Mapping XS 7dc43a60
END DESCRIPTION:
XS GIS Cut Line= 3
      1670205.23      7031628.19      1670125.35      7031416.34
      1670029.51      7031156.45
#Sta/Elev= 30
  4774.7 1468.67  4815.1 1467.51  4860.4 1463.56  4875.5 1463.02  4892.5 1460.71
  4900.4 1458.52  4905.7 1455.08  4913.8 1451.97  4924.5 1449.37  4935.9 1443.31
  4960.8 1435.09  4974.8 1432.43  4975.3 1431.93  4980.7 1431.93  4981.2 1432.43
  4985.6 1432.49  4991.0 1433.84  5010.0 1434.09  5031.3 1435.82  5041.1 1437.09
  5052.6 1439.88  5071.5 1441.63  5076.8 1443.12  5084.6 1444.23  5127.0 1448.77
  5137.9 1449.05  5169.9 1451.88  5218.4 1457.58  5233.8 1457.99  5278.1 1461.42
#Mann=3,-1,0
  4774.7    0.07       0  4974.8    0.07       0  4981.2    0.07       0
Bank Sta=4974.8,4981.2
Exp/Cntr=0.3,0.1

Type RM Length L Ch R = 1,4175,336,336,336
BEGIN DESCRIPTION:
Mapping XS 9df5165a
END DESCRIPTION:
XS GIS Cut Line= 3
      1670443.28      7031469.32      1670403.13      7031143.77
      1670348.88      7030883.38
#Sta/Elev= 30
  4671.5 1462.44  4713.1 1461.25  4753.4 1457.76  4773.6 1455.49  4779.3 1453.79
  4803.8 1451.11  4874.3 1445.26  4914.7 1440.19  4924.7 1438.05  4934.8 1434.60
  4941.6 1428.43  4951.7 1427.38  4952.2 1426.88  4958.2 1427.38  4965.0 1428.02
  4985.2 1427.52  4994.9 1428.59  5025.8 1427.74  5056.5 1432.46  5076.9 1437.19
  5097.3 1439.99  5107.6 1442.23  5112.8 1445.04  5148.4 1453.55  5157.7 1456.97
  5162.8 1457.84  5168.8 1460.72  5179.1 1462.55  5250.6 1466.41  5265.5 1466.36
#Mann=3,-1,0
  4671.5    0.07       0  4951.7    0.07       0  4958.2    0.07       0
Bank Sta=4951.7,4958.2
Exp/Cntr=0.3,0.1

Type RM Length L Ch R = 1,3839,245,245,245
BEGIN DESCRIPTION:
Mapping XS 41a30ebc
END DESCRIPTION:
XS GIS Cut Line= 3
      1670684.88      7031430.98      1670706.59      7031137.98
      1670718.52      7030876.45
#Sta/Elev= 30
  4702.5 1458.23  4805.8 1451.95  4855.9 1446.35  4909.1 1441.56  4926.1 1437.81
  4946.1 1431.64  4966.2 1426.78  4976.2 1424.91  4986.3 1424.05  4998.8 1423.97
  5006.3 1422.52  5013.0 1420.30  5013.5 1419.80  5019.0 1419.80  5019.5 1420.30
  5026.3 1420.97  5046.3 1424.92  5071.2 1427.65  5076.4 1428.84  5096.4 1430.54
  5102.9 1432.05  5136.4 1439.52  5146.4 1443.97  5176.5 1454.91  5196.5 1463.03
  5206.5 1466.15  5216.5 1467.82  5250.4 1469.39  5252.0 1469.46  5258.1 1469.58
#Mann=6,-1,0
  4702.5    0.07       0  5013.0    0.07       0  5019.5    0.07       0
  5102.9    0.16       0  5250.4   0.035       0  5252.0    0.07       0
Bank Sta=5013,5019.5
Exp/Cntr=0.3,0.1

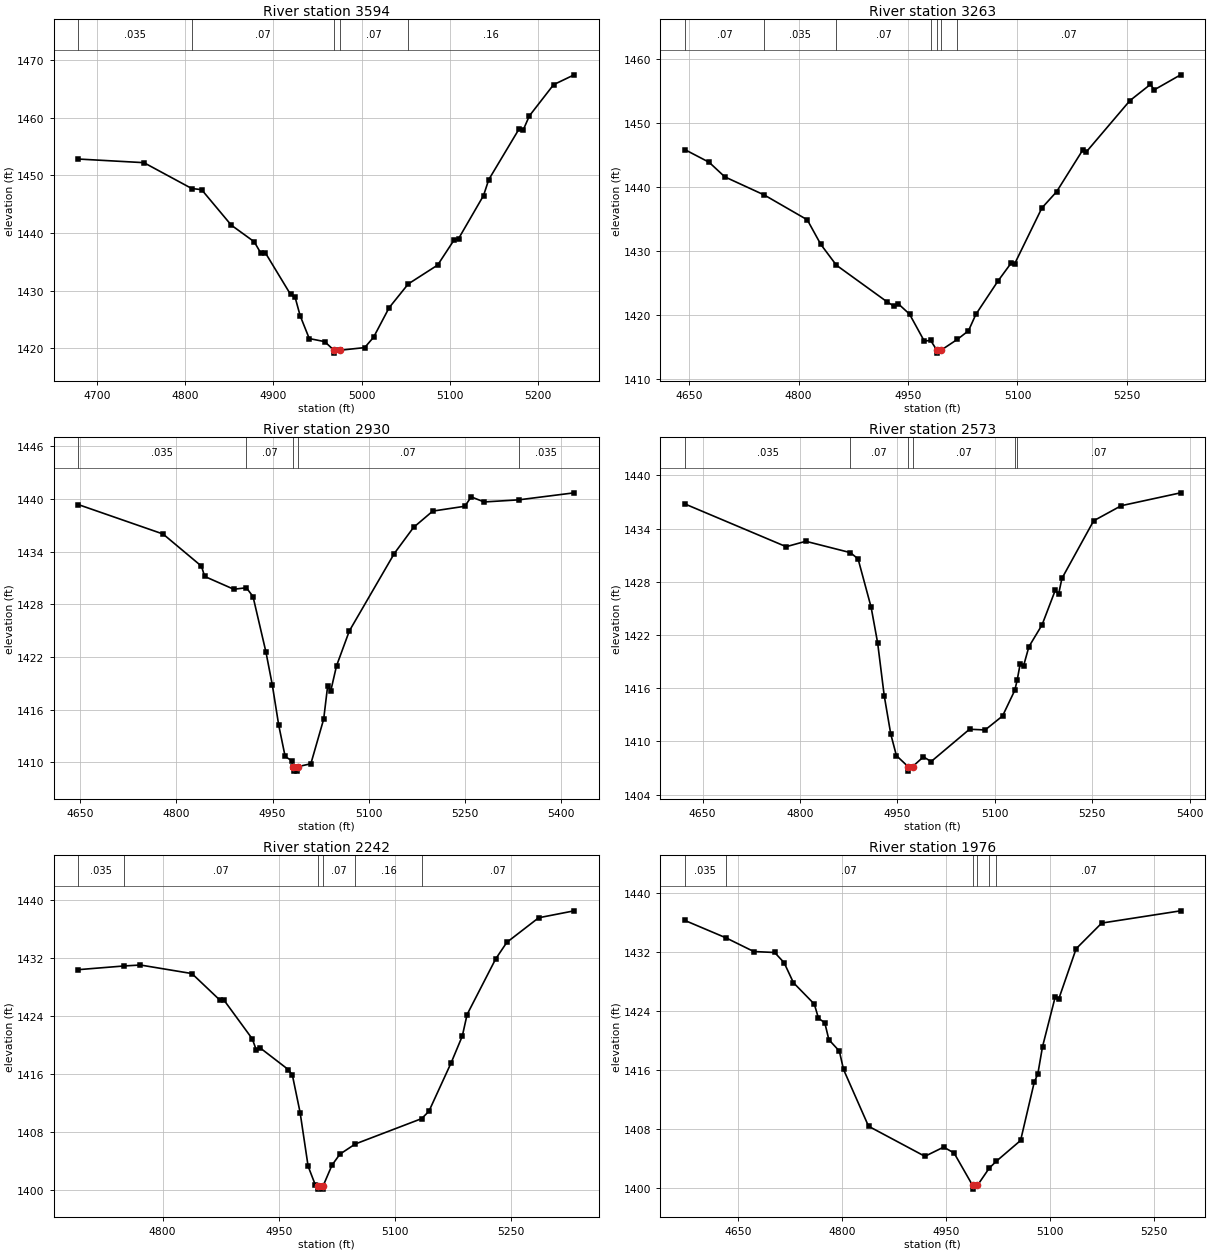
Type RM Length L Ch R = 1,3594,331,331,331
BEGIN DESCRIPTION:
Mapping XS bbc46064
END DESCRIPTION:
XS GIS Cut Line= 3
      1670861.76      7031449.39      1670950.73      7031142.32
      1671015.83      7030909.03
#Sta/Elev= 30
  4678.9 1452.86  4753.2 1452.23  4807.4 1447.74  4818.6 1447.54  4852.2 1441.38
  4878.2 1438.49  4885.8 1436.49  4891.0 1436.53  4919.4 1429.34  4924.6 1428.83
  4930.2 1425.67  4940.6 1421.67  4958.1 1421.14  4968.6 1419.64  4969.1 1419.14
  4975.2 1419.64  5003.4 1420.10  5013.5 1421.90  5031.1 1427.03  5052.8 1431.16
  5086.1 1434.44  5104.6 1438.77  5109.8 1439.03  5138.1 1446.52  5144.0 1449.28
  5178.1 1458.02  5183.3 1457.99  5190.0 1460.35  5217.5 1465.78  5240.8 1467.49
#Mann=5,-1,0
  4678.9   0.035       0  4807.4    0.07       0  4968.6    0.07       0
  4975.2    0.07       0  5052.8    0.16       0
Bank Sta=4968.6,4975.2
Exp/Cntr=0.3,0.1

Type RM Length L Ch R = 1,3263,333,333,333
BEGIN DESCRIPTION:
Mapping XS f45ee013
END DESCRIPTION:
XS GIS Cut Line= 3
      1671194.15      7031592.10      1671250.14      7031240.50
      1671283.99      7030918.90
#Sta/Elev= 30
  4644.2 1445.90  4677.5 1443.92  4699.0 1441.64  4753.2 1438.80  4812.0 1434.93
  4830.6 1431.08  4851.9 1427.84  4921.8 1422.08  4931.3 1421.41  4936.3 1421.85
  4952.1 1420.20  4972.4 1415.97  4981.0 1416.10  4989.3 1414.60  4989.8 1414.10
  4995.9 1414.60  5017.8 1416.26  5032.9 1417.59  5043.0 1420.15  5073.1 1425.33
  5091.3 1428.16  5096.3 1428.08  5133.5 1436.78  5153.6 1439.31  5189.3 1445.80
  5194.4 1445.54  5254.1 1453.55  5282.3 1456.09  5287.4 1455.23  5323.6 1457.58
#Mann=7,-1,0
  4644.2    0.07       0  4753.2   0.035       0  4851.9    0.07       0
  4981.0   0.035       0  4989.3   0.035       0  4995.9   0.035       0
  5017.8    0.07       0
Bank Sta=4989.3,4995.9
Exp/Cntr=0.3,0.1

Type RM Length L Ch R = 1,2930,357,357,357
BEGIN DESCRIPTION:
Mapping XS 975654f0
END DESCRIPTION:
XS GIS Cut Line= 3
      1671526.18      7031689.75      1671550.92      7031338.16
      1671540.51      7030917.55
#Sta/Elev= 30
  4647.1 1439.36  4779.2 1436.01  4839.1 1432.35  4844.1 1431.18  4889.5 1429.72
  4909.1 1429.89  4919.5 1428.89  4939.6 1422.59  4949.6 1418.82  4959.6 1414.24
  4969.6 1410.68  4979.7 1410.20  4982.2 1409.51  4982.7 1409.01  4988.4 1409.01
  4988.9 1409.51  5009.7 1409.85  5029.7 1414.93  5035.8 1418.65  5040.8 1418.16
  5049.7 1420.99  5069.7 1424.97  5139.8 1433.79  5169.8 1436.76  5199.8 1438.62
  5249.8 1439.17  5259.8 1440.24  5279.8 1439.66  5333.7 1439.90  5420.3 1440.70
#Mann=5,-1,0
  4647.1   0.035       0  4909.1    0.07       0  4982.2    0.07       0
  4988.9    0.07       0  5333.7   0.035       0
Bank Sta=4982.2,4988.9
Exp/Cntr=0.3,0.1

Type RM Length L Ch R = 1,2573,331,331,331
BEGIN DESCRIPTION:
Mapping XS d7ecb061
END DESCRIPTION:
XS GIS Cut Line= 3
      1671833.48      7031713.12      1671875.14      7031339.46
      1671942.84      7030957.99
#Sta/Elev= 30
  4622.6 1436.77  4778.7 1431.95  4808.9 1432.56  4877.6 1431.28  4889.4 1430.57
  4909.5 1425.12  4919.5 1421.11  4929.6 1415.18  4939.7 1410.84  4948.4 1408.41
  4966.5 1407.16  4967.0 1406.66  4973.2 1407.16  4990.0 1408.27  5001.9 1407.74
  5061.0 1411.38  5085.0 1411.30  5111.8 1412.87  5130.7 1415.77  5134.3 1416.90
  5139.0 1418.76  5144.1 1418.50  5152.4 1420.68  5172.7 1423.15  5193.0 1427.04
  5198.1 1426.59  5203.2 1428.37  5252.1 1434.87  5294.6 1436.57  5386.0 1438.02
#Mann=6,-1,0
  4622.6   0.035       0  4877.6    0.07       0  4966.5    0.07       0
  4973.2    0.07       0  5130.7    0.16       0  5134.3    0.07       0
Bank Sta=4966.5,4973.2
Exp/Cntr=0.3,0.1

Type RM Length L Ch R = 1,2242,266,266,266
BEGIN DESCRIPTION:
Mapping XS 6e53090e
END DESCRIPTION:
XS GIS Cut Line= 3
      1672265.00      7031585.72      1672190.77      7031284.90
      1672117.86      7030963.31
#Sta/Elev= 30
  4691.4 1430.39  4750.3 1430.90  4771.5 1431.03  4837.9 1429.85  4874.3 1426.15
  4879.4 1426.16  4915.7 1420.84  4920.9 1419.31  4926.0 1419.57  4962.4 1416.57
  4967.5 1415.82  4977.5 1410.64  4987.8 1403.23  4997.1 1400.64  5000.5 1400.56
  5001.0 1400.06  5006.9 1400.06  5007.4 1400.56  5018.6 1403.37  5028.8 1404.89
  5048.7 1406.30  5134.2 1409.80  5143.6 1410.81  5172.4 1417.54  5186.7 1421.21
  5192.9 1424.19  5229.8 1431.88  5244.2 1434.17  5285.2 1437.56  5331.0 1438.52
#Mann=6,-1,0
  4691.4   0.035       0  4750.3    0.07       0  5000.5    0.07       0
  5007.4    0.07       0  5048.7    0.16       0  5134.2    0.07       0
Bank Sta=5000.5,5007.4
Exp/Cntr=0.3,0.1

Type RM Length L Ch R = 1,1976,282,282,282
BEGIN DESCRIPTION:
Mapping XS 10d2c4f3
END DESCRIPTION:
XS GIS Cut Line= 3
      1672643.87      7031537.47      1672408.22      7031180.74
      1672307.25      7030911.49
#Sta/Elev= 30
  4573.5 1436.34  4632.8 1433.98  4673.0 1432.12  4703.1 1431.99  4716.7 1430.61
  4730.2 1427.89  4760.3 1424.99  4766.3 1423.07  4775.4 1422.46  4781.3 1420.16
  4796.4 1418.62  4802.4 1416.13  4838.5 1408.43  4919.8 1404.35  4946.9 1405.60
  4961.9 1404.79  4988.6 1400.40  4989.1 1399.90  4995.5 1400.40  5012.6 1402.75
  5022.9 1403.69  5057.8 1406.50  5077.4 1414.36  5082.7 1415.55  5089.4 1419.21
  5107.7 1425.96  5113.0 1425.73  5137.9 1432.50  5174.8 1435.98  5288.6 1437.64
#Mann=6,-1,0
  4573.5   0.035       0  4632.8    0.07       0  4988.6    0.07       0
  4995.5    0.07       0  5012.6    0.16       0  5022.9    0.07       0
Bank Sta=4988.6,4995.5
Exp/Cntr=0.3,0.1

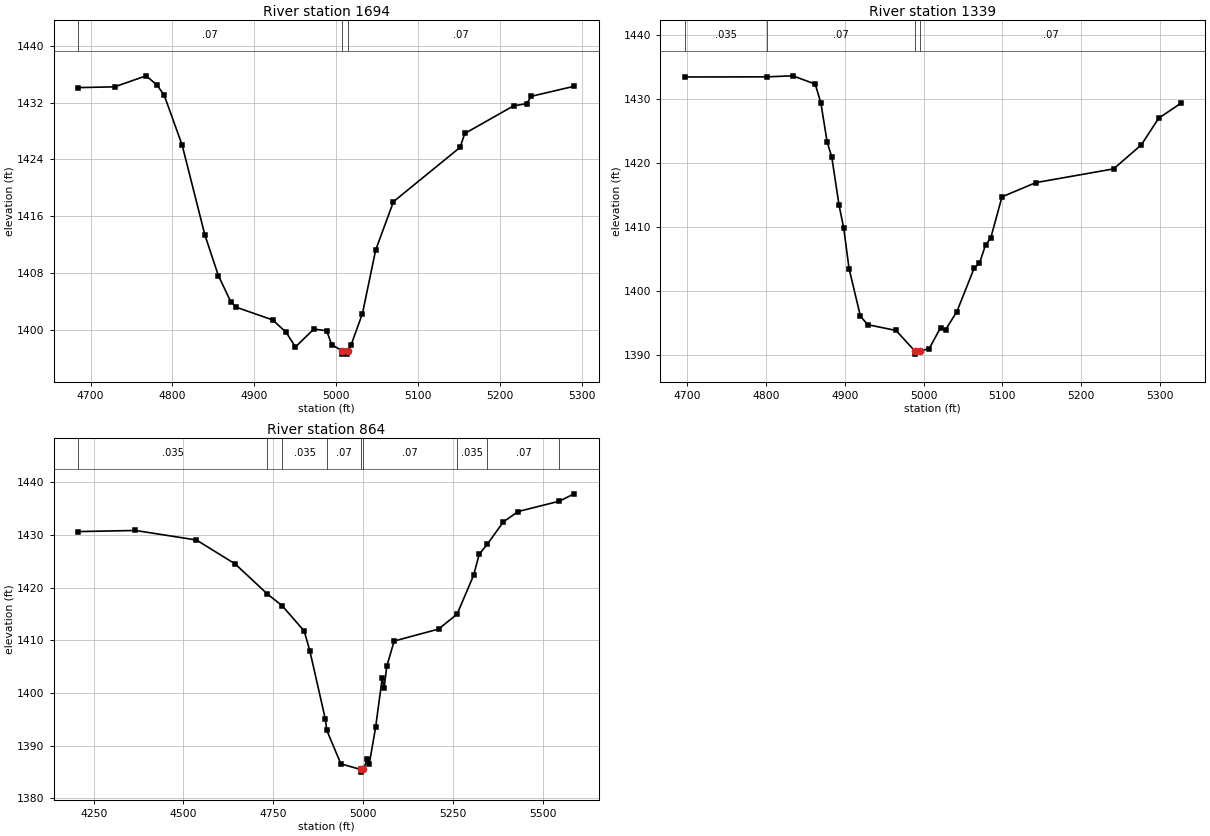
Type RM Length L Ch R = 1,1694,355,355,355
BEGIN DESCRIPTION:
Mapping XS 5a33f57a
END DESCRIPTION:
XS GIS Cut Line= 3
      1672800.14      7031363.02      1672654.31      7031084.38
      1672513.67      7030829.15
#Sta/Elev= 30
  4685.0 1434.11  4729.3 1434.22  4767.8 1435.77  4781.0 1434.49  4789.9 1433.05
  4811.9 1426.00  4839.6 1413.38  4856.1 1407.64  4871.2 1403.98  4878.1 1403.18
  4922.3 1401.40  4938.7 1399.69  4950.3 1397.58  4972.8 1400.11  4988.5 1399.87
  4994.6 1397.90  5007.0 1397.08  5007.5 1396.58  5013.5 1396.58  5014.0 1397.08
  5018.2 1397.83  5032.2 1402.30  5048.3 1411.22  5070.1 1418.05  5151.5 1425.70
  5157.2 1427.65  5216.8 1431.54  5232.9 1431.86  5238.6 1432.89  5290.9 1434.30
#Mann=3,-1,0
  4685.0    0.07       0  5007.0    0.07       0  5014.0    0.07       0
Bank Sta=5007,5014
Exp/Cntr=0.3,0.1

Type RM Length L Ch R = 1,1339,475,475,475
BEGIN DESCRIPTION:
Mapping XS 0b5b6189
END DESCRIPTION:
XS GIS Cut Line= 3
      1673179.97      7031032.30      1672924.75      7030866.93
      1672676.03      7030657.28
#Sta/Elev= 30
  4696.9 1433.39  4800.8 1433.41  4833.9 1433.57  4862.4 1432.29  4869.6 1429.37
  4877.6 1423.26  4883.5 1420.89  4892.7 1413.42  4898.7 1409.80  4905.4 1403.54
  4919.8 1396.13  4929.0 1394.80  4965.0 1393.90  4988.8 1390.71  4989.3 1390.21
  4995.9 1390.71  5007.2 1391.07  5021.5 1394.33  5028.0 1394.02  5042.3 1396.84
  5064.4 1403.66  5070.9 1404.35  5078.7 1407.24  5085.2 1408.27  5099.5 1414.71
  5142.4 1416.93  5241.2 1419.07  5276.4 1422.81  5298.4 1426.96  5326.3 1429.27
#Mann=4,-1,0
  4696.9   0.035       0  4800.8    0.07       0  4988.8    0.07       0
  4995.9    0.07       0
Bank Sta=4988.8,4995.9
Exp/Cntr=0.3,0.1

Type RM Length L Ch R = 1,864,0,0,0
BEGIN DESCRIPTION:
Mapping XS 279da498
END DESCRIPTION:
XS GIS Cut Line= 3
      1673455.84      7031125.62      1673058.75      7030439.55
      1672488.53      7030580.15
#Sta/Elev= 30
  4207.3 1430.66  4366.3 1430.87  4536.1 1429.06  4643.8 1424.51  4733.4 1418.81
  4774.6 1416.58  4836.0 1411.76  4851.6 1408.02  4894.9 1394.99  4898.8 1392.92
  4937.9 1386.55  4993.2 1385.47  4993.7 1384.97  5000.3 1385.47  5011.7 1387.49
  5016.9 1386.47  5034.8 1393.52  5053.2 1402.88  5058.3 1400.86  5065.7 1405.06
  5086.3 1409.87  5209.9 1412.14  5261.5 1414.98  5307.3 1422.33  5323.1 1426.36
  5346.0 1428.30  5390.2 1432.50  5431.7 1434.47  5545.8 1436.43  5587.3 1437.83
#Mann=9,-1,0
  4207.3   0.035       0  4733.4    0.07       0  4774.6   0.035       0
  4898.8    0.07       0  4993.2    0.07       0  5000.3    0.07       0
  5261.5   0.035       0  5346.0    0.07       0  5545.8   0.035       0
Bank Sta=4993.2,5000.3
Exp/Cntr=0.3,0.1

Chan Stop Cuts=-1