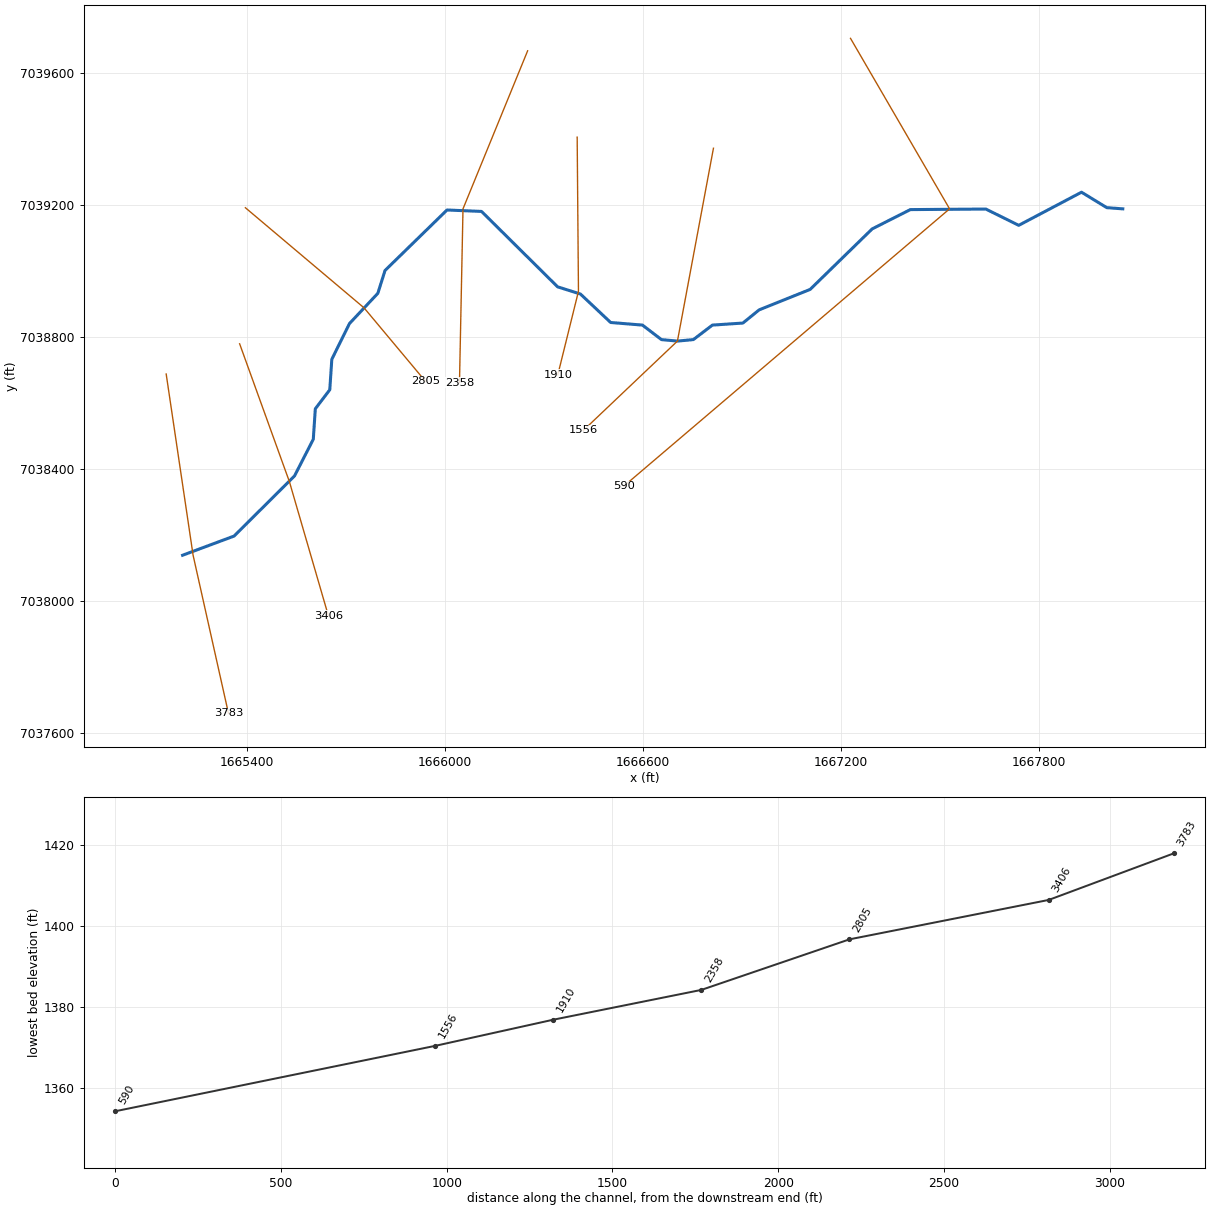
--- Chimney Creek 1186.prj (project) ---

Proj Title=Chimney Creek 1186 Base Level Engineering
Current Plan=p01
Default Exp/Contr=0.3,0.1
English Units
Geom File=g01
Flow File=f01
Plan File=p01
BEGIN DESCRIPTION:
Chimney Creek 1186
END DESCRIPTION:

--- Chimney Creek 1186.p01 (plan) ---

Plan Title=Multiple Run
Short Identifier=Multiple
Geom File=g01
Flow File=f01
Subcritical Flow
K Sum by GR= 0
Std Step Tol= 0.01
Critical Tol= 0.01
Num of Std Step Trials= 20
Max Error Tol= 0.3
Flow Tol Ratio= 0.001
Split Flow NTrial= 30
Split Flow Tol= 0.02
Split Flow Ratio= 0.02
Log Output Level= 0
Friction Slope Method= 1
Unsteady Friction Slope Method= 2
Unsteady Bridges Friction Slope Method= 1
Parabolic Critical Depth
Global Vel Dist=  1 , 1 , 1
Global Log Level= 0
CheckData=True
Encroach Param= -1, 0, 0, 0
BEGIN DESCRIPTION:
Multiple Run
END DESCRIPTION:

--- Chimney Creek 1186.f01 (steady flow) ---

Flow Title=Multiple
Number of Profiles=7
Profile Names=10-year,25-year,50-year,1pct_min,100-year,1pct_plu,500-year
River Rch & RM= Chimney Creek 11,Reach-1,3783
     377     546     693     439     875    1746    1415
River Rch & RM= Chimney Creek 11,Reach-1,2358
     546     805    1035     662    1322    2637    2185
Boundary for River Rch & Prof#=Chimney Creek 11,Reach-1,1
Up Type=0
Dn Type=3
Dn Slope=0.005
Boundary for River Rch & Prof#=Chimney Creek 11,Reach-1,2
Up Type=0
Dn Type=3
Dn Slope=0.005
Boundary for River Rch & Prof#=Chimney Creek 11,Reach-1,3
Up Type=0
Dn Type=3
Dn Slope=0.005
Boundary for River Rch & Prof#=Chimney Creek 11,Reach-1,4
Up Type=0
Dn Type=3
Dn Slope=0.005
Boundary for River Rch & Prof#=Chimney Creek 11,Reach-1,5
Up Type=0
Dn Type=3
Dn Slope=0.005
Boundary for River Rch & Prof#=Chimney Creek 11,Reach-1,6
Up Type=0
Dn Type=3
Dn Slope=0.005
Boundary for River Rch & Prof#=Chimney Creek 11,Reach-1,7
Up Type=0
Dn Type=3
Dn Slope=0.005

--- Chimney Creek 1186.g01 (geometry) ---

Geom Title=Existing Conditions

River Reach=Chimney Creek 11,Reach-1
Reach XY= 30
      1665205.00      7038138.00      1665361.06      7038196.13
      1665544.24      7038378.32      1665601.18      7038489.58
      1665607.35      7038582.03      1665651.15      7038639.60
      1665657.33      7038732.03      1665710.84      7038840.29
      1665796.82      7038931.96      1665818.63      7039001.21
      1666006.50      7039184.54      1666111.17      7039180.24
      1666341.79      7038951.63      1666411.04      7038929.82
      1666502.58      7038843.54      1666599.02      7038835.64
      1666656.60      7038791.70      1666705.00      7038787.18
      1666753.40      7038791.70      1666810.97      7038835.64
      1666903.42      7038841.83      1666952.82      7038881.88
      1667107.30      7038943.83      1667295.32      7039127.24
      1667410.93      7039185.76      1667639.79      7039187.46
      1667739.61      7039138.08      1667929.99      7039238.48
      1668006.49      7039191.69      1668055.00      7039188.00

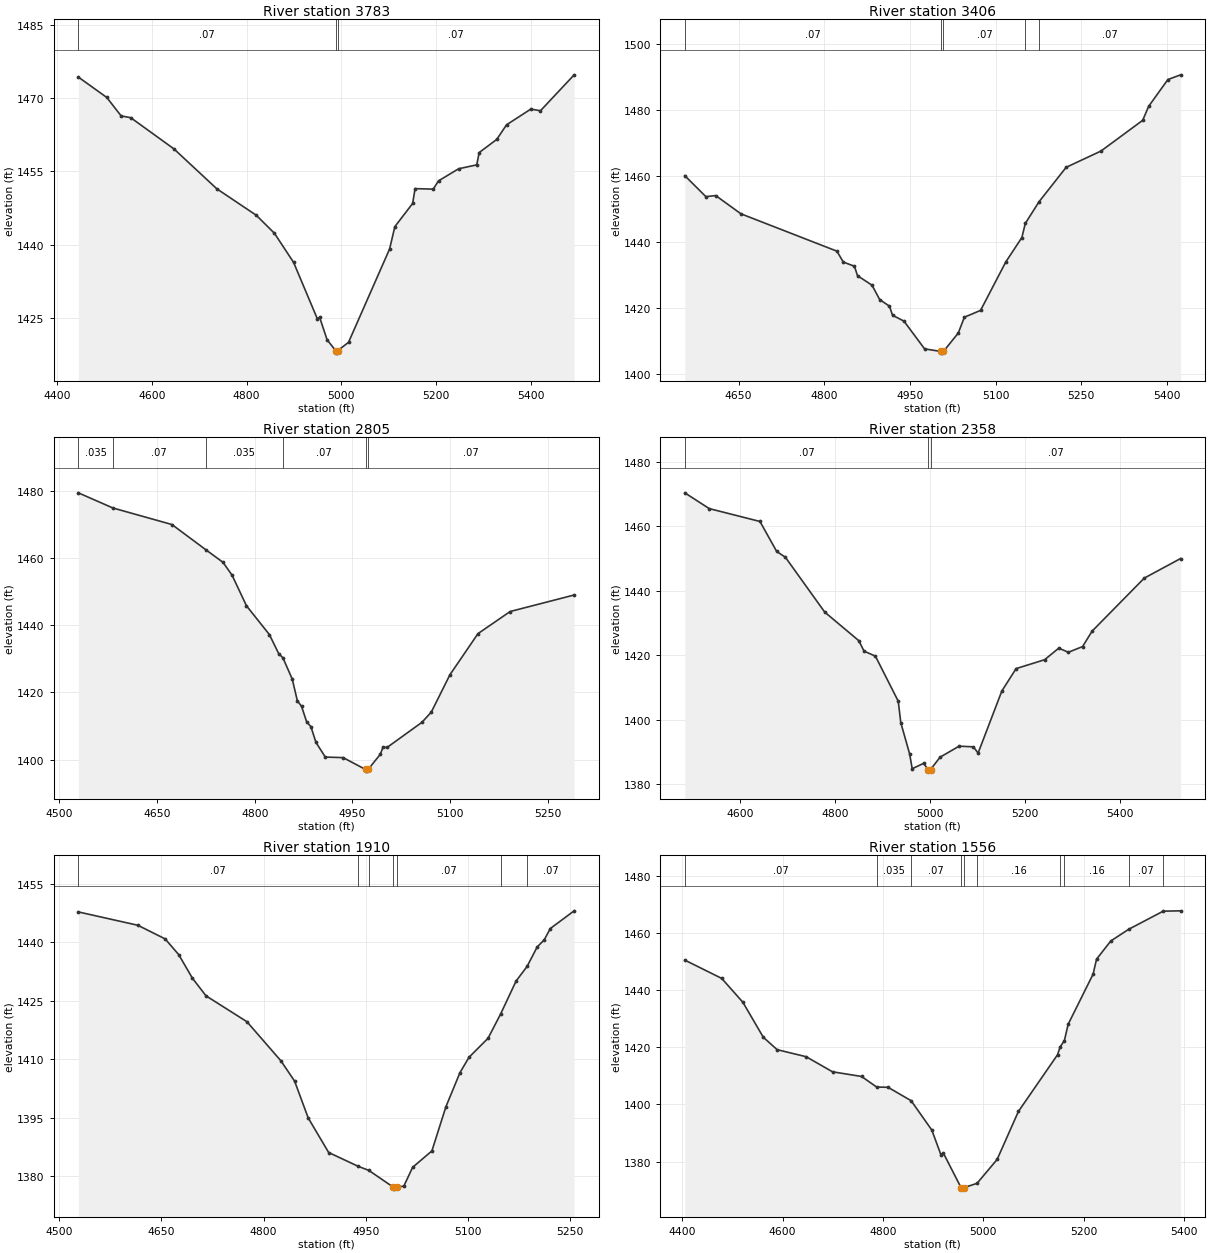
Type RM Length L Ch R = 1,3783,377,377,377
BEGIN DESCRIPTION:
Chimney Creek 1186 8.0
END DESCRIPTION:
XS GIS Cut Line= 3
      1665155.24      7038687.38      1665236.81      7038138.10
      1665344.06      7037658.65
#Sta/Elev= 30
  4444.7 1474.27  4504.7 1470.11  4535.1 1466.33  4555.3 1465.97  4646.3 1459.61
  4737.2 1451.42  4820.3 1446.03  4858.6 1442.35  4899.0 1436.41  4949.1 1424.89
  4954.1 1425.15  4969.8 1420.58  4988.0 1418.35  4988.2 1417.85  4992.0 1418.35
  5015.0 1420.05  5101.8 1439.15  5112.8 1443.70  5150.4 1448.45  5155.5 1451.47
  5193.8 1451.37  5205.0 1453.06  5247.4 1455.53  5285.7 1456.33  5290.8 1458.84
  5328.0 1461.54  5348.5 1464.51  5399.7 1467.72  5420.2 1467.39  5491.3 1474.73
#Mann=3,-1,0
  4444.7    0.07       0  4988.0    0.07       0  4992.0    0.07       0
Bank Sta=4988,4992
Exp/Cntr=0.3,0.1

Type RM Length L Ch R = 1,3406,601,601,601
BEGIN DESCRIPTION:
Chimney Creek 1186 7.0
END DESCRIPTION:
XS GIS Cut Line= 3
      1665377.91      7038778.89      1665528.71      7038361.18
      1665647.01      7037954.22
#Sta/Elev= 30
  4555.9 1460.10  4592.8 1453.74  4610.0 1454.07  4654.1 1448.55  4822.2 1437.23
  4833.3 1433.94  4852.9 1432.66  4858.2 1429.81  4883.6 1426.93  4897.1 1422.56
  4914.2 1420.57  4919.5 1417.83  4939.6 1416.04  4975.6 1407.65  5004.6 1406.86
  5004.8 1406.36  5008.6 1406.86  5034.6 1412.45  5045.3 1417.24  5073.6 1419.30
  5117.9 1434.01  5145.9 1441.35  5151.9 1445.63  5176.1 1452.23  5223.4 1462.62
  5284.5 1467.56  5357.4 1476.86  5367.9 1481.11  5401.5 1489.20  5423.8 1490.63
#Mann=5,-1,0
  4555.9    0.07       0  5004.6    0.07       0  5008.6    0.07       0
  5151.9    0.16       0  5176.1    0.07       0
Bank Sta=5004.6,5008.6
Exp/Cntr=0.3,0.1

Type RM Length L Ch R = 1,2805,447,447,447
BEGIN DESCRIPTION:
Chimney Creek 1186 6.0
END DESCRIPTION:
XS GIS Cut Line= 3
      1665395.30      7039191.43      1665755.00      7038888.00
      1665941.07      7038665.41
#Sta/Elev= 30
  4529.4 1479.33  4582.5 1474.82  4673.0 1469.91  4724.7 1462.46  4751.4 1458.67
  4765.3 1454.84  4787.4 1445.75  4822.5 1437.22  4836.8 1431.55  4843.3 1430.30
  4857.6 1423.97  4865.4 1417.55  4871.9 1415.86  4879.7 1411.27  4886.2 1409.85
  4894.0 1405.16  4908.3 1400.81  4935.7 1400.64  4970.0 1397.13  4970.3 1396.63
  4974.0 1397.13  4992.8 1401.66  4996.7 1403.68  5003.2 1403.68  5056.6 1411.14
  5070.9 1414.16  5099.5 1425.27  5142.5 1437.48  5191.9 1444.06  5290.1 1448.97
#Mann=6,-1,0
  4529.4   0.035       0  4582.5    0.07       0  4724.7   0.035       0
  4843.3    0.07       0  4970.0    0.07       0  4974.0    0.07       0
Bank Sta=4970,4974
Exp/Cntr=0.3,0.1

Type RM Length L Ch R = 1,2358,448,448,448
BEGIN DESCRIPTION:
Chimney Creek 1186 5.0
END DESCRIPTION:
XS GIS Cut Line= 3
      1666250.93      7039667.14      1666055.00      7039188.00
      1666044.35      7038661.56
#Sta/Elev= 30
  4483.3 1470.41  4534.8 1465.52  4641.6 1461.53  4676.8 1452.24  4695.1 1450.45
  4777.9 1433.45  4849.7 1424.58  4860.8 1421.34  4884.8 1419.77  4932.8 1405.82
  4938.2 1399.16  4956.8 1389.47  4962.2 1384.89  4986.2 1386.55  4995.7 1384.64
  4996.1 1384.14  5000.8 1384.64  5021.0 1388.47  5061.0 1391.88  5091.0 1391.67
  5101.0 1389.74  5151.0 1408.98  5181.0 1415.92  5241.0 1418.67  5271.0 1422.27
  5291.0 1420.98  5321.0 1422.75  5341.0 1427.52  5451.0 1443.98  5527.5 1450.05
#Mann=3,-1,0
  4483.3    0.07       0  4995.7    0.07       0  5000.8    0.07       0
Bank Sta=4995.7,5000.8
Exp/Cntr=0.3,0.1

Type RM Length L Ch R = 1,1910,354,354,354
BEGIN DESCRIPTION:
Chimney Creek 1186 4.0
END DESCRIPTION:
XS GIS Cut Line= 3
      1666401.10      7039405.38      1666405.00      7038938.00
      1666342.49      7038685.31
#Sta/Elev= 30
  4528.2 1447.75  4615.6 1444.33  4655.6 1440.84  4675.6 1436.80  4695.6 1430.78
  4715.6 1426.26  4775.6 1419.64  4825.6 1409.60  4845.6 1404.42  4865.6 1394.98
  4895.6 1386.14  4938.7 1382.62  4954.5 1381.56  4990.5 1377.26  4990.9 1376.76
  4995.7 1377.26  5005.9 1377.53  5018.9 1382.36  5047.1 1386.54  5067.7 1397.87
  5088.3 1406.59  5101.7 1410.55  5129.5 1415.39  5147.8 1421.55  5170.7 1430.06
  5186.8 1433.78  5201.6 1438.77  5211.9 1440.58  5220.9 1443.50  5255.9 1448.03
#Mann=7,-1,0
  4528.2    0.07       0  4938.7   0.035       0  4954.5    0.07       0
  4990.5    0.07       0  4995.7    0.07       0  5147.8    0.16       0
  5186.8    0.07       0
Bank Sta=4990.5,4995.7
Exp/Cntr=0.3,0.1

Type RM Length L Ch R = 1,1556,966,966,966
BEGIN DESCRIPTION:
Chimney Creek 1186 3.0
END DESCRIPTION:
XS GIS Cut Line= 3
      1666814.18      7039371.77      1666705.00      7038787.18
      1666419.84      7038516.47
#Sta/Elev= 30
  4405.3 1450.58  4478.9 1444.16  4521.0 1435.81  4561.7 1423.55  4589.3 1419.20
  4647.1 1416.73  4699.7 1411.44  4757.5 1409.81  4787.6 1406.10  4810.2 1406.02
  4856.2 1401.33  4897.4 1391.05  4915.5 1382.44  4920.6 1382.92  4955.8 1370.84
  4956.2 1370.34  4961.2 1370.84  4987.6 1372.37  5027.6 1380.74  5070.0 1397.55
  5148.0 1417.43  5153.2 1420.19  5161.6 1422.37  5169.1 1428.10  5218.8 1445.65
  5225.7 1450.91  5254.0 1457.27  5289.7 1461.37  5358.5 1467.72  5393.2 1467.84
#Mann=10,-1,0
  4405.3    0.07       0  4787.6   0.035       0  4856.2    0.07       0
  4955.8    0.07       0  4961.2    0.07       0  4987.6    0.16       0
  5153.2    0.07       0  5161.6    0.16       0  5289.7    0.07       0
  5358.5    0.16       0
Bank Sta=4955.8,4961.2
Exp/Cntr=0.3,0.1

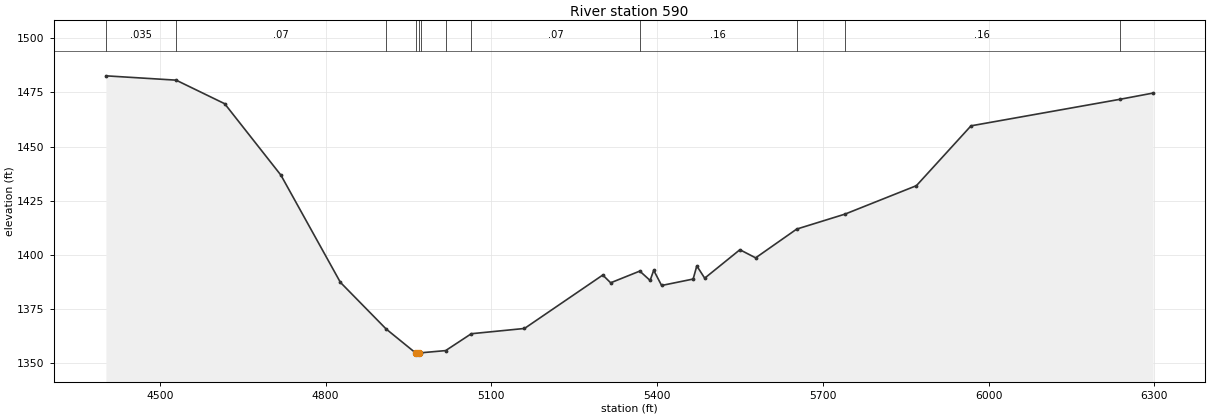
Type RM Length L Ch R = 1,590,0,0,0
BEGIN DESCRIPTION:
Chimney Creek 1186 2.0
END DESCRIPTION:
XS GIS Cut Line= 3
      1667229.65      7039704.92      1667530.00      7039188.05
      1666542.01      7038346.99
#Sta/Elev= 30
  4402.2 1482.69  4529.3 1480.69  4617.2 1469.81  4719.0 1436.81  4826.6 1387.33
  4909.4 1365.79  4963.0 1354.68  4963.4 1354.18  4968.4 1354.68  4972.2 1354.79
  5017.1 1355.81  5063.6 1363.60  5159.8 1366.03  5301.5 1390.70  5315.8 1387.12
  5368.5 1392.52  5387.2 1388.20  5393.7 1392.89  5408.0 1385.88  5465.1 1388.85
  5471.7 1394.92  5486.0 1389.25  5549.7 1402.39  5578.2 1398.64  5652.5 1411.92
  5739.9 1418.83  5869.2 1431.97  5968.0 1459.60  6237.1 1471.83  6297.5 1474.73
#Mann=12,-1,0
  4402.2   0.035       0  4529.3    0.07       0  4909.4   0.035       0
  4963.0    0.07       0  4968.4   0.035       0  4972.2    0.07       0
  5017.1   0.035       0  5063.6    0.07       0  5368.5    0.16       0
  5652.5    0.07       0  5739.9    0.16       0  6237.1    0.07       0
Bank Sta=4963,4968.4
Exp/Cntr=0.3,0.1

Chan Stop Cuts=-1