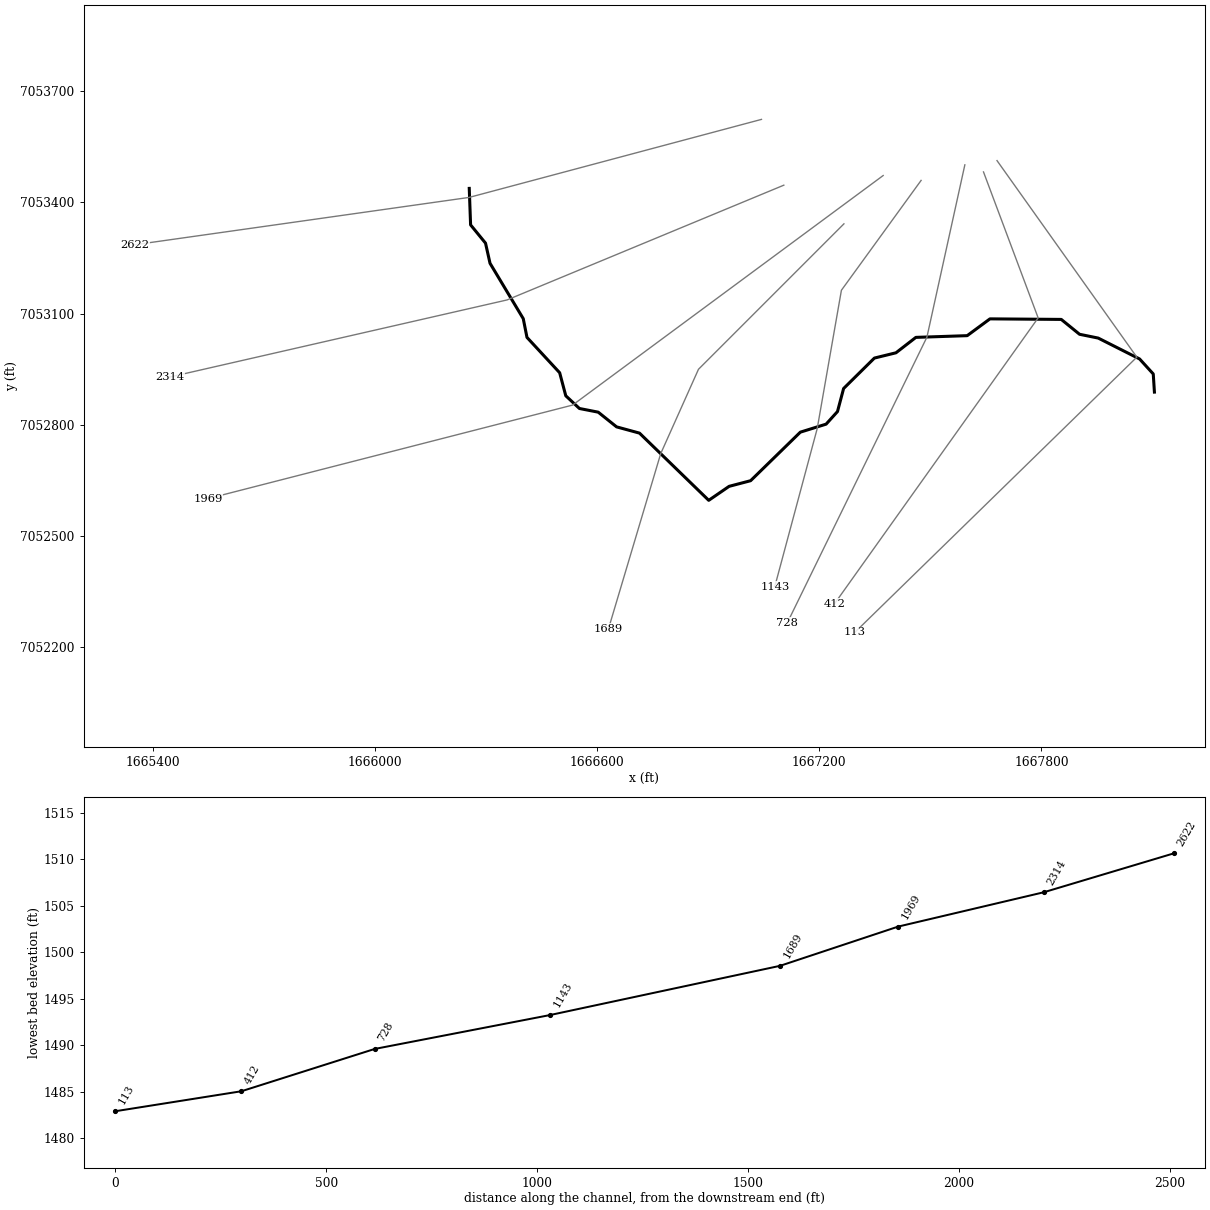
--- Chimney Creek 1188.prj (project) ---

Proj Title=Chimney Creek 1188 Base Level Engineering
Current Plan=p01
Default Exp/Contr=0.3,0.1
English Units
Geom File=g01
Flow File=f01
Plan File=p01
BEGIN DESCRIPTION:
Chimney Creek 1188
END DESCRIPTION:

--- Chimney Creek 1188.p01 (plan) ---

Plan Title=Multiple Run
Short Identifier=Multiple
Geom File=g01
Flow File=f01
Subcritical Flow
K Sum by GR= 0
Std Step Tol= 0.01
Critical Tol= 0.01
Num of Std Step Trials= 20
Max Error Tol= 0.3
Flow Tol Ratio= 0.001
Split Flow NTrial= 30
Split Flow Tol= 0.02
Split Flow Ratio= 0.02
Log Output Level= 0
Friction Slope Method= 1
Unsteady Friction Slope Method= 2
Unsteady Bridges Friction Slope Method= 1
Parabolic Critical Depth
Global Vel Dist=  1 , 1 , 1
Global Log Level= 0
CheckData=True
Encroach Param= -1, 0, 0, 0
BEGIN DESCRIPTION:
Multiple Run
END DESCRIPTION:

--- Chimney Creek 1188.f01 (steady flow) ---

Flow Title=Multiple
Number of Profiles=7
Profile Names=10-year,25-year,50-year,1pct_min,100-year,1pct_plu,500-year
River Rch & RM= Chimney Creek 11,Reach-1,2622
     323     454     564     349     697    1390    1069
River Rch & RM= Chimney Creek 11,Reach-1,2314
     546     792    1005     634    1264    2522    2019
Boundary for River Rch & Prof#=Chimney Creek 11,Reach-1,1
Up Type=0
Dn Type=3
Dn Slope=0.005
Boundary for River Rch & Prof#=Chimney Creek 11,Reach-1,2
Up Type=0
Dn Type=3
Dn Slope=0.005
Boundary for River Rch & Prof#=Chimney Creek 11,Reach-1,3
Up Type=0
Dn Type=3
Dn Slope=0.005
Boundary for River Rch & Prof#=Chimney Creek 11,Reach-1,4
Up Type=0
Dn Type=3
Dn Slope=0.005
Boundary for River Rch & Prof#=Chimney Creek 11,Reach-1,5
Up Type=0
Dn Type=3
Dn Slope=0.005
Boundary for River Rch & Prof#=Chimney Creek 11,Reach-1,6
Up Type=0
Dn Type=3
Dn Slope=0.005
Boundary for River Rch & Prof#=Chimney Creek 11,Reach-1,7
Up Type=0
Dn Type=3
Dn Slope=0.005

--- Chimney Creek 1188.g01 (geometry) ---

Geom Title=Existing Conditions

River Reach=Chimney Creek 11,Reach-1
Reach XY= 30
      1666255.00      7053438.00      1666258.63      7053339.50
      1666298.91      7053290.19      1666311.08      7053235.80
      1666400.81      7053086.26      1666410.85      7053035.71
      1666499.12      7052940.26      1666515.65      7052878.00
      1666552.45      7052843.73      1666603.24      7052833.80
      1666652.81      7052794.10      1666714.68      7052777.24
      1666901.59      7052595.77      1666956.65      7052633.53
      1667014.68      7052648.75      1667148.97      7052779.83
      1667218.56      7052801.49      1667249.25      7052835.46
      1667265.78      7052897.68      1667348.93      7052979.87
      1667407.17      7052994.14      1667460.93      7053035.75
      1667599.47      7053040.39      1667660.94      7053085.74
      1667853.45      7053084.25      1667902.82      7053044.12
      1667953.28      7053033.84      1668064.98      7052977.45
      1668101.86      7052936.97      1668105.00      7052888.00

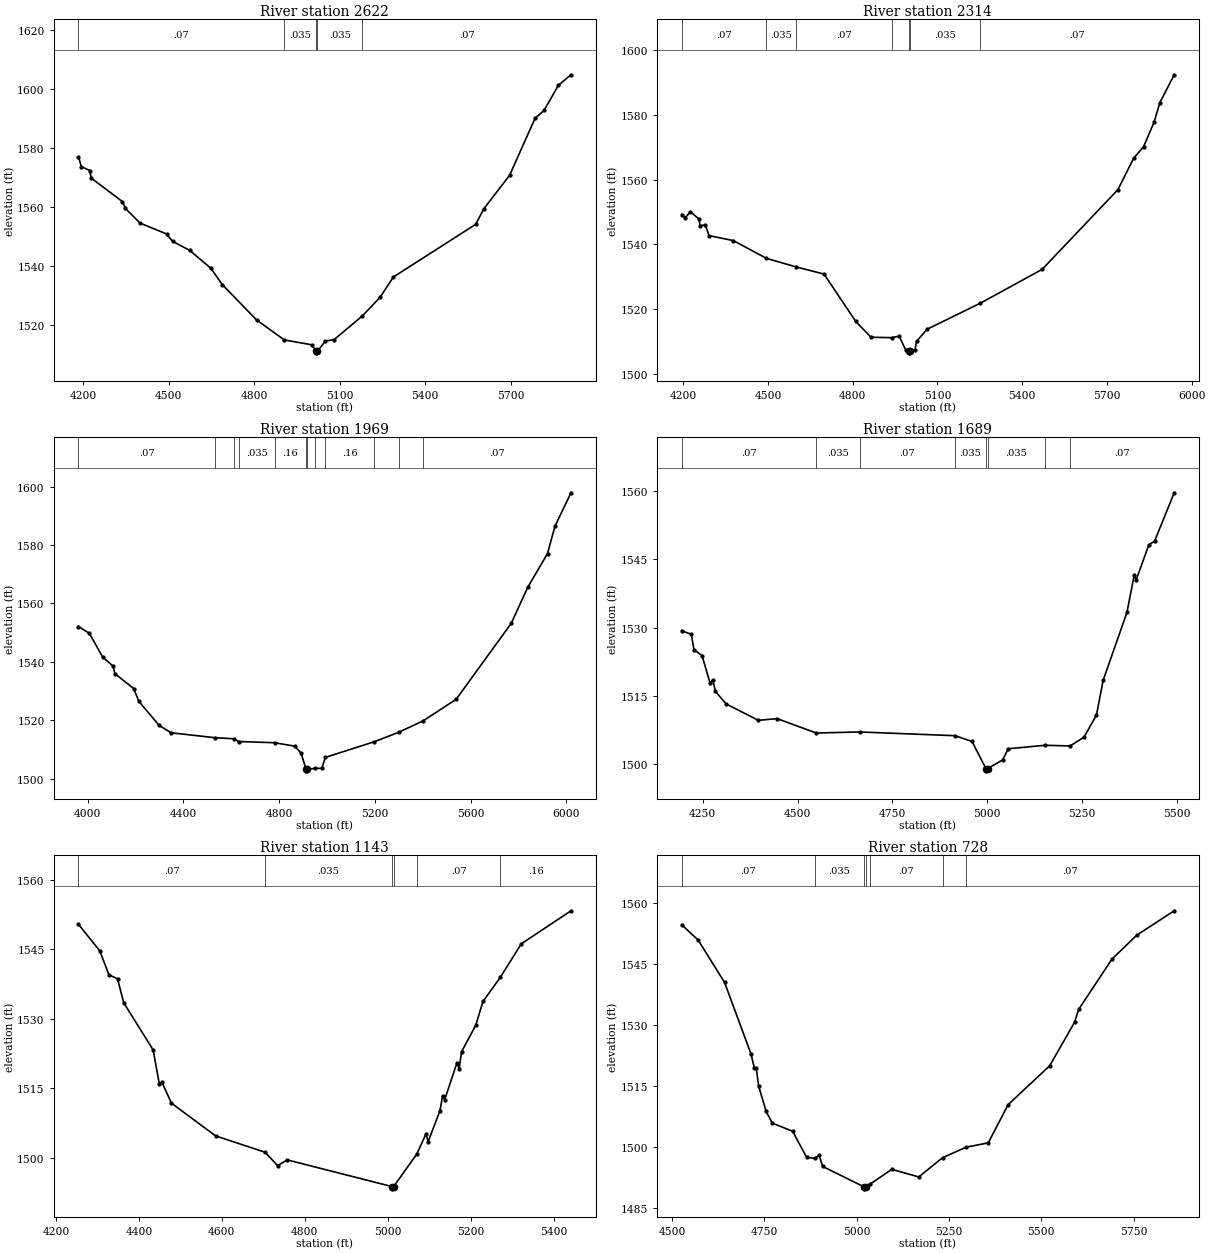
Type RM Length L Ch R = 1,2622,308,308,308
BEGIN DESCRIPTION:
Chimney Creek 1188 5.0
END DESCRIPTION:
XS GIS Cut Line= 3
      1667044.00      7053624.32      1666254.73      7053413.67
      1665351.24      7053285.76
#Sta/Elev= 30
  4183.1 1577.01  4192.9 1573.68  4222.6 1572.31  4227.8 1569.77  4337.3 1561.81
  4348.1 1559.48  4399.4 1554.54  4492.6 1550.85  4513.3 1548.37  4573.1 1545.34
  4647.8 1539.27  4688.2 1533.71  4808.5 1521.76  4905.6 1515.02  5002.4 1513.35
  5017.9 1511.14  5018.2 1510.64  5021.9 1511.14  5050.2 1514.64  5080.8 1515.11
  5179.9 1523.14  5242.1 1529.44  5288.9 1536.31  5578.0 1554.14  5605.7 1559.30
  5696.6 1570.67  5786.0 1589.95  5817.8 1592.66  5868.3 1601.19  5912.5 1604.72
#Mann=5,-1,0
  4183.1    0.07       0  4905.6   0.035       0  5017.9   0.035       0
  5021.9   0.035       0  5179.9    0.07       0
Bank Sta=5017.9,5021.9
Exp/Cntr=0.3,0.1

Type RM Length L Ch R = 1,2314,345,345,345
BEGIN DESCRIPTION:
Mapping XS 78357c4c
END DESCRIPTION:
XS GIS Cut Line= 3
      1667104.33      7053446.68      1666356.98      7053136.81
      1665445.53      7052928.48
#Sta/Elev= 30
  4194.2 1549.21  4206.8 1548.24  4225.2 1550.06  4254.5 1547.93  4259.9 1545.80
  4278.4 1545.99  4290.9 1542.72  4377.5 1541.15  4494.6 1535.66  4600.6 1533.00
  4698.4 1530.81  4810.5 1516.18  4864.7 1511.28  4937.6 1511.15  4964.2 1511.61
  4988.1 1507.27  4999.4 1506.96  4999.7 1506.46  5003.8 1506.96  5020.5 1507.46
  5025.8 1510.00  5063.5 1513.77  5251.7 1521.80  5470.6 1532.27  5738.6 1556.89
  5795.1 1566.69  5829.6 1570.16  5866.9 1577.75  5887.5 1583.83  5938.2 1592.43
#Mann=7,-1,0
  4194.2    0.07       0  4494.6   0.035       0  4600.6    0.07       0
  4937.6   0.035       0  4999.4   0.035       0  5003.8   0.035       0
  5251.7    0.07       0
Bank Sta=4999.4,5003.8
Exp/Cntr=0.3,0.1

Type RM Length L Ch R = 1,1969,280,280,280
BEGIN DESCRIPTION:
Mapping XS 13f3675d
END DESCRIPTION:
XS GIS Cut Line= 3
      1667372.60      7053472.74      1666534.06      7052852.95
      1665549.88      7052600.40
#Sta/Elev= 30
  3961.1 1552.11  4006.4 1549.81  4062.7 1541.63  4106.6 1538.53  4112.8 1536.03
  4192.2 1530.90  4213.0 1526.56  4298.6 1518.28  4348.7 1515.78  4531.7 1514.10
  4609.9 1513.74  4630.9 1512.80  4780.7 1512.38  4864.4 1511.22  4891.5 1508.85
  4912.3 1503.27  4912.6 1502.77  4916.7 1503.27  4951.5 1503.64  4977.8 1503.62
  4993.0 1507.37  5197.8 1512.73  5299.4 1515.95  5401.0 1519.83  5539.7 1527.23
  5770.0 1553.21  5839.1 1565.56  5921.7 1577.08  5952.7 1586.43  6019.9 1597.86
#Mann=12,-1,0
  3961.1    0.07       0  4531.7   0.035       0  4609.9    0.07       0
  4630.9   0.035       0  4780.7    0.16       0  4912.3    0.07       0
  4916.7    0.16       0  4951.5    0.07       0  4993.0    0.16       0
  5197.8    0.07       0  5299.4    0.16       0  5401.0    0.07       0
Bank Sta=4912.3,4916.7
Exp/Cntr=0.3,0.1

Type RM Length L Ch R = 1,1689,546,546,546
BEGIN DESCRIPTION:
Mapping XS 603e6e0f
END DESCRIPTION:
XS GIS Cut Line= 4
      1667266.67      7053342.34      1666873.90      7052949.56
      1666771.90      7052721.70      1666630.84      7052248.60
#Sta/Elev= 30
  4194.5 1529.33  4220.0 1528.54  4227.0 1525.15  4248.2 1523.88  4269.5 1517.78
  4276.5 1518.53  4283.6 1515.98  4311.9 1513.25  4396.7 1509.64  4446.2 1510.02
  4549.2 1506.86  4663.8 1507.09  4915.2 1506.27  4960.3 1505.00  4996.7 1499.05
  4997.0 1498.55  5001.1 1499.05  5040.6 1500.93  5055.7 1503.40  5152.1 1504.16
  5218.9 1504.02  5255.2 1505.92  5288.3 1510.79  5306.1 1518.47  5368.7 1533.35
  5387.8 1541.50  5393.0 1540.49  5426.2 1548.15  5441.7 1549.03  5493.3 1559.63
#Mann=8,-1,0
  4194.5    0.07       0  4549.2   0.035       0  4663.8    0.07       0
  4915.2   0.035       0  4996.7   0.035       0  5001.1   0.035       0
  5152.1    0.16       0  5218.9    0.07       0
Bank Sta=4996.7,5001.1
Exp/Cntr=0.3,0.1

Type RM Length L Ch R = 1,1143,415,415,415
BEGIN DESCRIPTION:
Mapping XS fa44a8b9
END DESCRIPTION:
XS GIS Cut Line= 4
      1667475.04      7053459.57      1667259.84      7053162.96
      1667194.51      7052789.49      1667080.00      7052362.99
#Sta/Elev= 30
  4254.4 1550.43  4305.8 1544.69  4327.7 1539.53  4348.6 1538.64  4363.3 1533.49
  4434.4 1523.27  4449.1 1515.98  4455.2 1516.37  4478.5 1511.76  4585.1 1504.69
  4704.1 1501.16  4734.2 1498.29  4757.9 1499.50  5009.6 1493.75  5009.9 1493.25
  5014.2 1493.75  5069.9 1500.79  5092.0 1505.13  5097.2 1503.46  5125.8 1510.15
  5132.0 1513.37  5137.2 1512.56  5166.8 1520.52  5172.0 1519.26  5177.6 1522.85
  5212.0 1528.63  5229.3 1533.75  5271.4 1539.00  5321.6 1546.21  5441.6 1553.36
#Mann=6,-1,0
  4254.4    0.07       0  4704.1   0.035       0  5009.6   0.035       0
  5014.2   0.035       0  5069.9    0.07       0  5271.4    0.16       0
Bank Sta=5009.6,5014.2
Exp/Cntr=0.3,0.1

Type RM Length L Ch R = 1,728,316,316,316
BEGIN DESCRIPTION:
Mapping XS 161c5935
END DESCRIPTION:
XS GIS Cut Line= 3
      1667593.15      7053501.59      1667490.72      7053036.29
      1667113.99      7052265.47
#Sta/Elev= 30
  4525.7 1554.63  4570.3 1550.88  4642.0 1540.42  4713.7 1522.78  4722.6 1519.40
  4727.7 1519.45  4734.2 1514.94  4754.6 1508.66  4771.5 1505.78  4826.3 1503.79
  4864.1 1497.39  4886.4 1497.09  4898.0 1497.87  4907.8 1495.12  5019.4 1490.11
  5019.7 1489.61  5024.1 1490.11  5035.8 1490.75  5094.9 1494.42  5168.0 1492.54
  5232.5 1497.27  5296.3 1499.86  5356.4 1500.93  5410.1 1510.33  5522.7 1519.91
  5590.1 1530.61  5601.4 1533.81  5691.4 1546.15  5759.0 1552.09  5860.1 1558.07
#Mann=7,-1,0
  4525.7    0.07       0  4886.4   0.035       0  5019.4   0.035       0
  5024.1   0.035       0  5035.8    0.07       0  5232.5   0.035       0
  5296.3    0.07       0
Bank Sta=5019.4,5024.1
Exp/Cntr=0.3,0.1

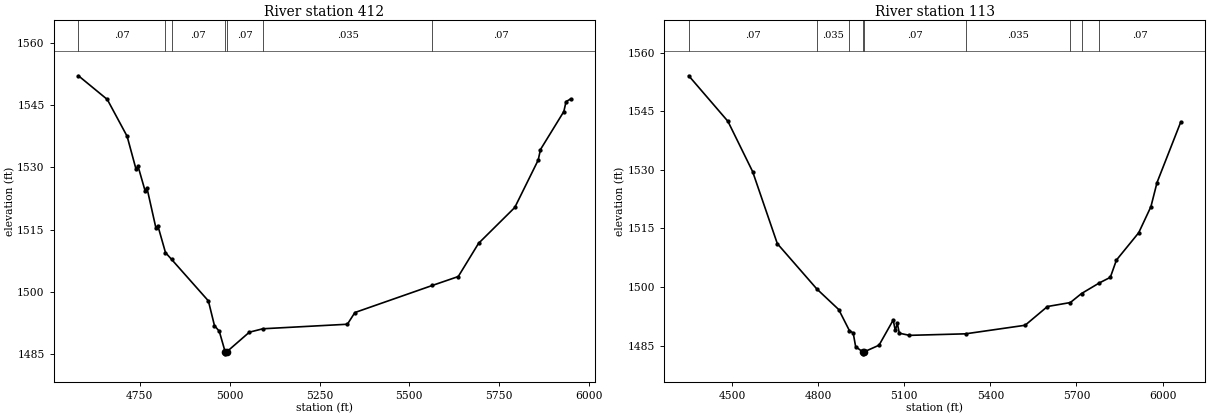
Type RM Length L Ch R = 1,412,299,299,299
BEGIN DESCRIPTION:
Mapping XS 2ad6e29c
END DESCRIPTION:
XS GIS Cut Line= 3
      1667643.49      7053482.47      1667791.07      7053088.37
      1667240.71      7052315.78
#Sta/Elev= 30
  4579.1 1552.04  4659.3 1546.34  4714.5 1537.47  4739.5 1529.47  4744.8 1530.29
  4764.4 1524.37  4769.7 1525.03  4794.7 1515.36  4800.0 1515.94  4821.3 1509.45
  4838.2 1507.82  4940.7 1497.81  4957.6 1491.86  4971.0 1490.50  4987.3 1485.56
  4987.6 1485.06  4992.0 1485.56  5054.6 1490.27  5092.4 1491.10  5327.5 1492.19
  5348.4 1495.01  5563.8 1501.53  5636.1 1503.68  5692.6 1511.68  5793.4 1520.32
  5858.6 1531.74  5864.8 1534.26  5929.9 1543.43  5936.1 1545.82  5948.5 1546.44
#Mann=7,-1,0
  4579.1    0.07       0  4821.3   0.035       0  4838.2    0.07       0
  4987.3    0.07       0  4992.0    0.07       0  5092.4   0.035       0
  5563.8    0.07       0
Bank Sta=4987.3,4992
Exp/Cntr=0.3,0.1

Type RM Length L Ch R = 1,113,0,0,0
BEGIN DESCRIPTION:
Chimney Creek 1188 1.0
END DESCRIPTION:
XS GIS Cut Line= 3
      1667679.98      7053513.03      1668057.52      7052982.32
      1667296.26      7052239.39
#Sta/Elev= 30
  4348.7 1554.05  4485.2 1542.40  4571.3 1529.54  4657.4 1511.10  4795.2 1499.50
  4871.4 1494.24  4908.8 1488.83  4921.8 1488.26  4930.4 1484.74  4955.1 1483.41
  4955.4 1482.91  4959.8 1483.41  5011.9 1485.12  5061.3 1491.56  5068.5 1488.89
  5075.5 1490.68  5082.7 1488.19  5117.9 1487.64  5313.3 1488.03  5521.0 1490.22
  5598.9 1495.02  5678.6 1496.03  5717.6 1498.34  5780.2 1501.07  5818.0 1502.48
  5839.3 1506.90  5917.0 1513.90  5959.5 1520.56  5980.8 1526.74  6063.7 1542.26
#Mann=9,-1,0
  4348.7    0.07       0  4795.2   0.035       0  4908.8    0.07       0
  4955.1    0.07       0  4959.8    0.07       0  5313.3   0.035       0
  5678.6    0.07       0  5717.6   0.035       0  5780.2    0.07       0
Bank Sta=4955.1,4959.8
Exp/Cntr=0.3,0.1

Chan Stop Cuts=-1