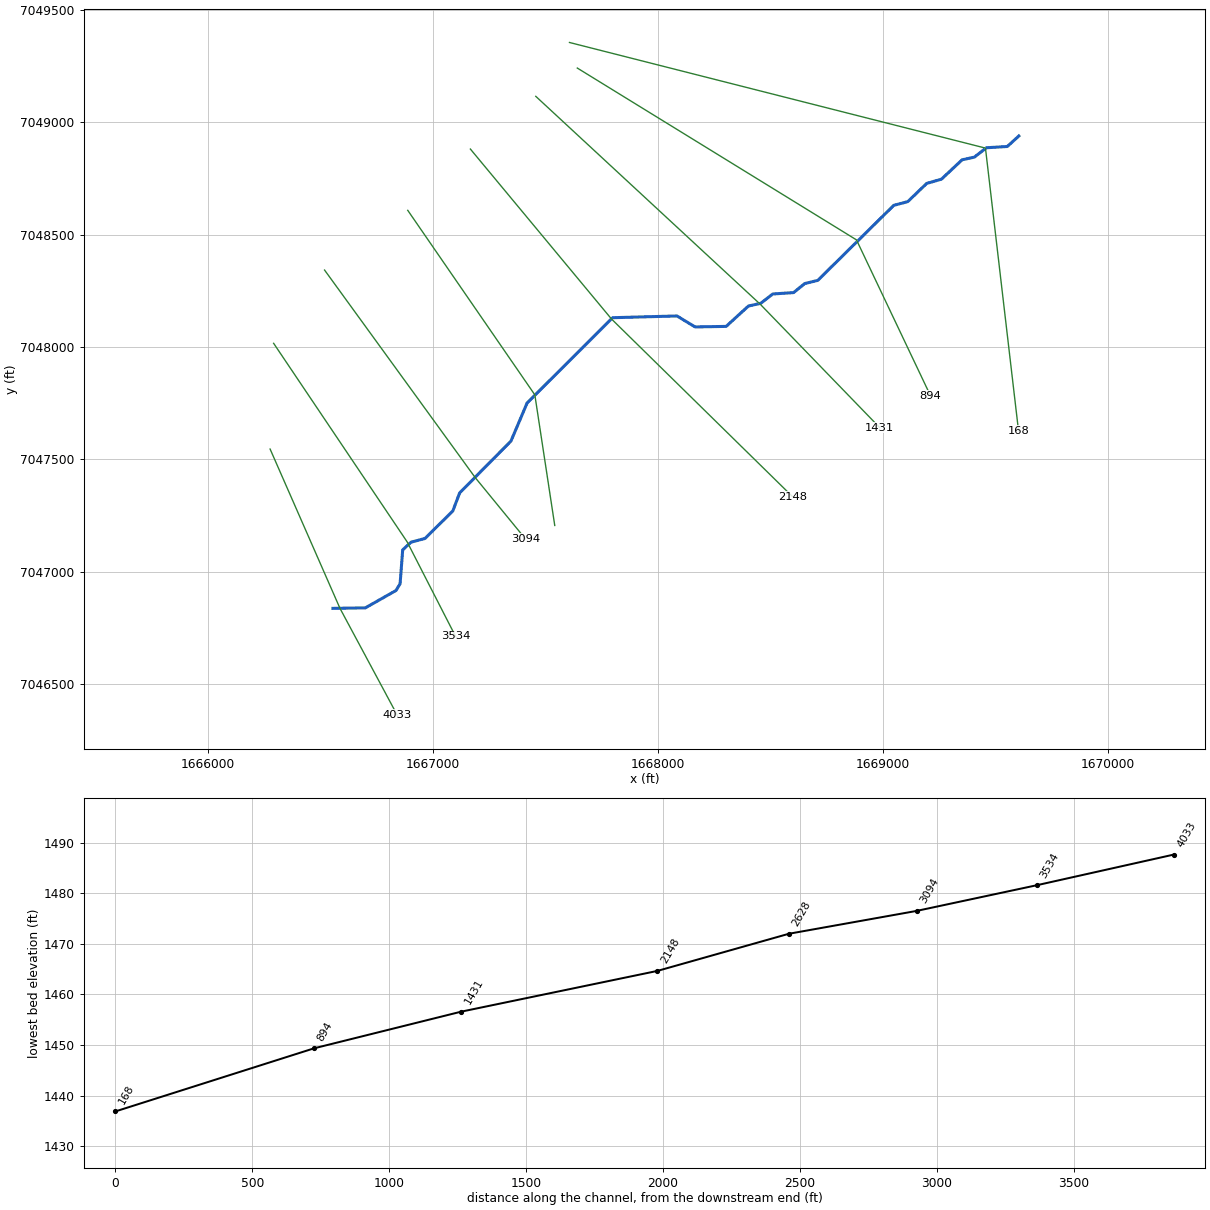
--- Chimney Creek 1189.prj (project) ---

Proj Title=Chimney Creek 1189 Base Level Engineering
Current Plan=p01
Default Exp/Contr=0.3,0.1
English Units
Geom File=g01
Flow File=f01
Plan File=p01
BEGIN DESCRIPTION:
Chimney Creek 1189
END DESCRIPTION:

--- Chimney Creek 1189.p01 (plan) ---

Plan Title=Multiple Run
Short Identifier=Multiple
Geom File=g01
Flow File=f01
Subcritical Flow
K Sum by GR= 0
Std Step Tol= 0.01
Critical Tol= 0.01
Num of Std Step Trials= 20
Max Error Tol= 0.3
Flow Tol Ratio= 0.001
Split Flow NTrial= 30
Split Flow Tol= 0.02
Split Flow Ratio= 0.02
Log Output Level= 0
Friction Slope Method= 1
Unsteady Friction Slope Method= 2
Unsteady Bridges Friction Slope Method= 1
Parabolic Critical Depth
Global Vel Dist=  1 , 1 , 1
Global Log Level= 0
CheckData=True
Encroach Param= -1, 0, 0, 0
BEGIN DESCRIPTION:
Multiple Run
END DESCRIPTION:

--- Chimney Creek 1189.f01 (steady flow) ---

Flow Title=Multiple
Number of Profiles=7
Profile Names=10-year,25-year,50-year,1pct_min,100-year,1pct_plu,500-year
River Rch & RM= Chimney Creek 11,Reach-1,4033
     317     450     564     352     702    1401    1103
River Rch & RM= Chimney Creek 11,Reach-1,2628
     392     563     710     446     891    1777    1418
Boundary for River Rch & Prof#=Chimney Creek 11,Reach-1,1
Up Type=0
Dn Type=3
Dn Slope=0.005
Boundary for River Rch & Prof#=Chimney Creek 11,Reach-1,2
Up Type=0
Dn Type=3
Dn Slope=0.005
Boundary for River Rch & Prof#=Chimney Creek 11,Reach-1,3
Up Type=0
Dn Type=3
Dn Slope=0.005
Boundary for River Rch & Prof#=Chimney Creek 11,Reach-1,4
Up Type=0
Dn Type=3
Dn Slope=0.005
Boundary for River Rch & Prof#=Chimney Creek 11,Reach-1,5
Up Type=0
Dn Type=3
Dn Slope=0.005
Boundary for River Rch & Prof#=Chimney Creek 11,Reach-1,6
Up Type=0
Dn Type=3
Dn Slope=0.005
Boundary for River Rch & Prof#=Chimney Creek 11,Reach-1,7
Up Type=0
Dn Type=3
Dn Slope=0.005

--- Chimney Creek 1189.g01 (geometry) ---

Geom Title=Existing Conditions

River Reach=Chimney Creek 11,Reach-1
Reach XY= 30
      1666555.00      7046838.00      1666699.50      7046840.31
      1666835.56      7046917.45      1666853.85      7046947.44
      1666865.35      7047098.12      1666902.43      7047132.26
      1666964.66      7047148.79      1667088.35      7047271.33
      1667118.63      7047351.21      1667346.86      7047581.94
      1667418.62      7047751.21      1667798.81      7048130.19
      1668084.97      7048137.93      1668165.51      7048089.21
      1668303.53      7048091.54      1668402.71      7048182.15
      1668457.17      7048194.14      1668510.97      7048235.67
      1668603.42      7048241.83      1668652.83      7048281.86
      1668711.06      7048296.14      1669048.95      7048629.84
      1669111.04      7048646.18      1669195.33      7048727.20
      1669261.04      7048746.18      1669352.71      7048832.16
      1669407.17      7048844.14      1669460.95      7048885.70
      1669553.60      7048891.39      1669605.00      7048938.00

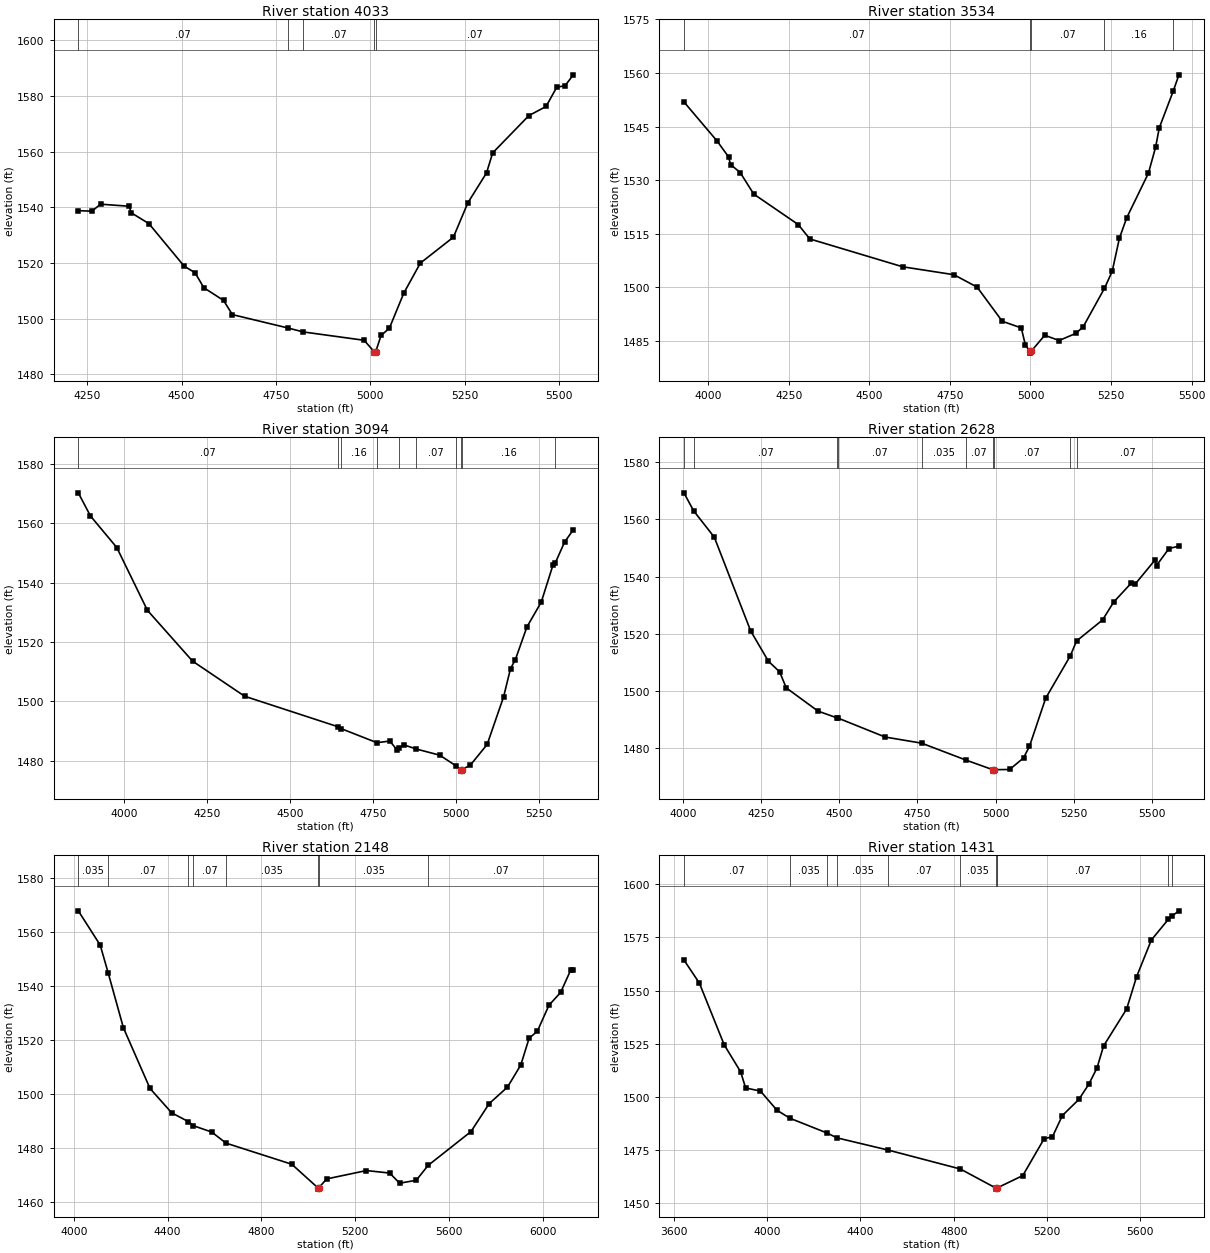
Type RM Length L Ch R = 1,4033,499,499,499
BEGIN DESCRIPTION:
Chimney Creek 1189 8.0
END DESCRIPTION:
XS GIS Cut Line= 3
      1666275.86      7047546.25      1666586.61      7046837.92
      1666840.73      7046364.29
#Sta/Elev= 30
  4226.5 1538.80  4262.3 1538.61  4285.6 1541.12  4361.2 1540.38  4366.6 1538.04
  4413.4 1534.15  4506.8 1518.88  4535.7 1516.51  4559.0 1511.12  4611.2 1506.56
  4634.6 1501.47  4782.3 1496.65  4821.8 1495.26  4983.5 1492.25  5010.1 1488.14
  5010.3 1487.64  5014.1 1488.14  5028.3 1493.98  5050.2 1496.56  5088.4 1509.15
  5132.3 1519.96  5219.9 1529.27  5258.1 1541.59  5307.6 1552.35  5323.9 1559.54
  5419.8 1572.93  5465.2 1576.20  5493.6 1583.12  5515.5 1583.66  5537.5 1587.57
#Mann=5,-1,0
  4226.5    0.07       0  4782.3   0.035       0  4821.8    0.07       0
  5010.1    0.07       0  5014.1    0.07       0
Bank Sta=5010.1,5014.1
Exp/Cntr=0.3,0.1

Type RM Length L Ch R = 1,3534,440,440,440
BEGIN DESCRIPTION:
Mapping XS d789d7ec
END DESCRIPTION:
XS GIS Cut Line= 3
      1666291.47      7048016.42      1666885.21      7047133.62
      1667100.35      7046713.72
#Sta/Elev= 30
  3924.9 1551.93  4027.6 1541.00  4063.6 1536.52  4069.6 1534.39  4099.6 1532.14
  4141.6 1526.12  4279.6 1517.59  4315.6 1513.56  4603.5 1505.77  4762.5 1503.55
  4834.5 1500.08  4912.5 1490.52  4971.5 1488.66  4984.1 1483.92  4998.0 1482.10
  4998.3 1481.60  5002.0 1482.10  5044.4 1486.60  5088.8 1485.13  5141.2 1487.14
  5163.7 1488.99  5229.6 1499.75  5253.5 1504.47  5276.0 1513.78  5298.5 1519.46
  5365.9 1531.96  5388.4 1539.30  5399.6 1544.65  5442.9 1554.95  5460.6 1559.50
#Mann=5,-1,0
  3924.9    0.07       0  4998.0    0.07       0  5002.0    0.07       0
  5229.6    0.16       0  5442.9    0.07       0
Bank Sta=4998,5002
Exp/Cntr=0.3,0.1

Type RM Length L Ch R = 1,3094,466,466,466
BEGIN DESCRIPTION:
Mapping XS 0d1bcb0b
END DESCRIPTION:
XS GIS Cut Line= 3
      1666518.02      7048341.96      1667187.30      7047420.08
      1667410.65      7047147.38
#Sta/Elev= 30
  3861.0 1570.30  3897.6 1562.51  3977.1 1551.85  4069.2 1530.71  4205.3 1513.58
  4362.2 1501.75  4642.4 1491.51  4652.8 1490.84  4761.0 1486.09  4799.7 1486.65
  4820.6 1483.78  4828.1 1484.27  4842.1 1485.36  4879.6 1483.96  4950.5 1481.87
  4998.1 1478.36  5012.8 1477.01  5013.1 1476.51  5016.8 1477.01  5042.1 1478.50
  5093.0 1485.49  5142.6 1501.57  5163.4 1511.07  5177.7 1513.99  5212.9 1525.12
  5256.0 1533.47  5291.1 1545.88  5297.8 1546.55  5326.3 1553.70  5352.7 1557.87
#Mann=10,-1,0
  3861.0    0.07       0  4642.4   0.035       0  4652.8    0.16       0
  4761.0    0.07       0  4828.1    0.16       0  4879.6    0.07       0
  4998.1    0.16       0  5012.8    0.07       0  5016.8    0.16       0
  5297.8    0.07       0
Bank Sta=5012.8,5016.8
Exp/Cntr=0.3,0.1

Type RM Length L Ch R = 1,2628,480,480,480
BEGIN DESCRIPTION:
Mapping XS 3ee6cb00
END DESCRIPTION:
XS GIS Cut Line= 3
      1666887.82      7048607.57      1667452.92      7047787.26
      1667541.47      7047206.49
#Sta/Elev= 30
  4003.0 1569.32  4034.4 1562.99  4100.3 1553.80  4216.7 1521.00  4273.5 1510.41
  4309.3 1506.72  4330.3 1501.13  4431.7 1493.01  4493.6 1490.58  4495.0 1490.59
  4646.8 1483.92  4763.5 1481.78  4903.9 1475.92  4991.0 1472.50  4991.3 1472.00
  4995.1 1472.50  5045.0 1472.57  5089.4 1476.61  5108.5 1480.67  5160.2 1497.47
  5239.0 1512.29  5259.1 1517.51  5342.3 1524.87  5377.8 1531.11  5433.3 1537.66
  5446.3 1537.36  5509.9 1545.81  5514.9 1543.90  5554.7 1549.85  5586.6 1550.67
#Mann=10,-1,0
  4003.0   0.035       0  4034.4    0.07       0  4493.6   0.035       0
  4495.0    0.07       0  4763.5   0.035       0  4903.9    0.07       0
  4991.0    0.07       0  4995.1    0.07       0  5239.0    0.16       0
  5259.1    0.07       0
Bank Sta=4991,4995.1
Exp/Cntr=0.3,0.1

Type RM Length L Ch R = 1,2148,717,717,717
BEGIN DESCRIPTION:
Mapping XS 8f5a0985
END DESCRIPTION:
XS GIS Cut Line= 3
      1667166.35      7048879.96      1667793.55      7048124.72
      1668598.64      7047334.82
#Sta/Elev= 30
  4019.4 1567.91  4112.7 1555.21  4146.7 1544.90  4211.7 1524.50  4325.0 1502.01
  4417.4 1492.97  4487.9 1489.73  4509.6 1488.19  4588.0 1485.84  4649.0 1481.72
  4929.2 1473.89  5040.2 1465.16  5040.5 1464.66  5044.4 1465.16  5077.6 1468.44
  5247.3 1471.55  5346.3 1470.62  5388.8 1466.86  5459.5 1467.94  5510.3 1473.47
  5692.8 1486.01  5770.6 1496.41  5848.4 1502.51  5904.9 1510.68  5940.4 1520.61
  5975.7 1523.26  6025.2 1532.90  6074.7 1537.61  6117.1 1545.79  6129.0 1545.94
#Mann=8,-1,0
  4019.4   0.035       0  4146.7    0.07       0  4487.9   0.035       0
  4509.6    0.07       0  4649.0   0.035       0  5040.2   0.035       0
  5044.4   0.035       0  5510.3    0.07       0
Bank Sta=5040.2,5044.4
Exp/Cntr=0.3,0.1

Type RM Length L Ch R = 1,1431,537,537,537
BEGIN DESCRIPTION:
Mapping XS c00dd772
END DESCRIPTION:
XS GIS Cut Line= 3
      1667457.18      7049114.30      1668455.44      7048189.82
      1668986.03      7047641.90
#Sta/Elev= 30
  3642.8 1564.44  3709.2 1553.53  3815.8 1524.46  3886.1 1511.81  3907.6 1504.19
  3971.1 1502.75  4042.0 1493.72  4097.6 1489.95  4257.2 1482.98  4299.3 1480.72
  4518.8 1474.98  4828.6 1466.07  4980.8 1457.10  4981.2 1456.60  4985.5 1457.10
  4985.6 1457.12  5096.3 1462.98  5188.1 1480.34  5223.6 1481.23  5266.1 1491.23
  5336.8 1498.79  5379.2 1505.90  5414.5 1513.56  5442.8 1523.95  5541.8 1541.34
  5584.3 1556.49  5647.8 1573.82  5721.3 1583.62  5735.3 1585.00  5766.1 1587.54
#Mann=11,-1,0
  3642.8    0.07       0  4097.6   0.035       0  4257.2    0.07       0
  4299.3   0.035       0  4518.8    0.07       0  4828.6   0.035       0
  4980.8    0.07       0  4985.5   0.035       0  4985.6    0.07       0
  5721.3    0.16       0  5735.3    0.07       0
Bank Sta=4980.8,4985.5
Exp/Cntr=0.3,0.1

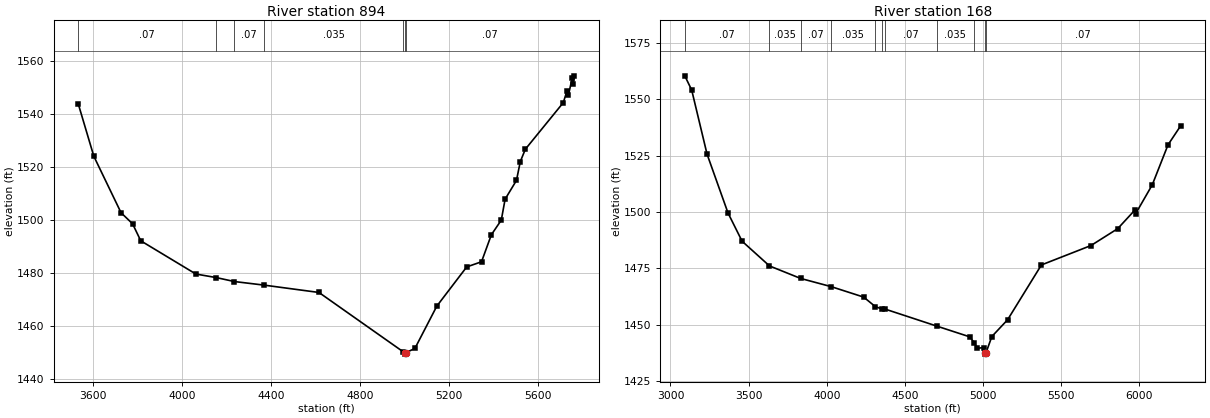
Type RM Length L Ch R = 1,894,726,726,726
BEGIN DESCRIPTION:
Mapping XS 4e4eeb4f
END DESCRIPTION:
XS GIS Cut Line= 3
      1667641.77      7049240.05      1668883.07      7048476.17
      1669212.62      7047782.38
#Sta/Elev= 30
  3534.9 1543.71  3604.4 1524.04  3726.6 1502.73  3778.4 1498.54  3815.1 1492.13
  4062.4 1479.59  4153.9 1478.25  4235.6 1476.75  4368.1 1475.41  4615.0 1472.63
  4994.3 1450.17  4999.1 1449.86  4999.4 1449.36  5003.8 1449.86  5045.7 1451.51
  5144.1 1467.49  5278.2 1482.27  5344.7 1484.22  5388.9 1494.42  5433.4 1499.93
  5450.6 1507.84  5501.6 1514.94  5518.8 1522.04  5541.5 1526.70  5711.7 1544.27
  5728.8 1548.82  5734.4 1547.00  5751.6 1553.50  5757.1 1551.26  5760.5 1554.39
#Mann=7,-1,0
  3534.9    0.07       0  4153.9   0.035       0  4235.6    0.07       0
  4368.1   0.035       0  4994.3    0.07       0  4999.1    0.07       0
  5003.8    0.07       0
Bank Sta=4999.1,5003.8
Exp/Cntr=0.3,0.1

Type RM Length L Ch R = 1,168,0,0,0
BEGIN DESCRIPTION:
Chimney Creek 1189 1.0
END DESCRIPTION:
XS GIS Cut Line= 3
      1667606.95      7049353.78      1669456.57      7048884.20
      1669603.48      7047628.06
#Sta/Elev= 30
  3091.7 1560.39  3135.8 1554.09  3234.1 1525.63  3368.3 1499.51  3458.3 1486.99
  3633.7 1476.02  3833.3 1470.46  4029.1 1466.82  4236.4 1462.19  4311.7 1457.92
  4355.1 1456.91  4375.0 1456.83  4704.6 1449.31  4915.8 1444.54  4942.4 1442.01
  4963.3 1439.47  5006.2 1439.81  5013.9 1437.38  5014.3 1436.88  5018.7 1437.38
  5056.6 1444.69  5157.3 1452.12  5373.8 1476.46  5690.9 1485.07  5862.0 1492.56
  5972.1 1500.82  5977.1 1499.24  6083.5 1512.06  6184.2 1529.79  6264.7 1538.18
#Mann=11,-1,0
  3091.7    0.07       0  3633.7   0.035       0  3833.3    0.07       0
  4029.1   0.035       0  4311.7    0.07       0  4355.1   0.035       0
  4375.0    0.07       0  4704.6   0.035       0  4942.4    0.07       0
  5013.9    0.07       0  5018.7    0.07       0
Bank Sta=5013.9,5018.7
Exp/Cntr=0.3,0.1

Chan Stop Cuts=-1