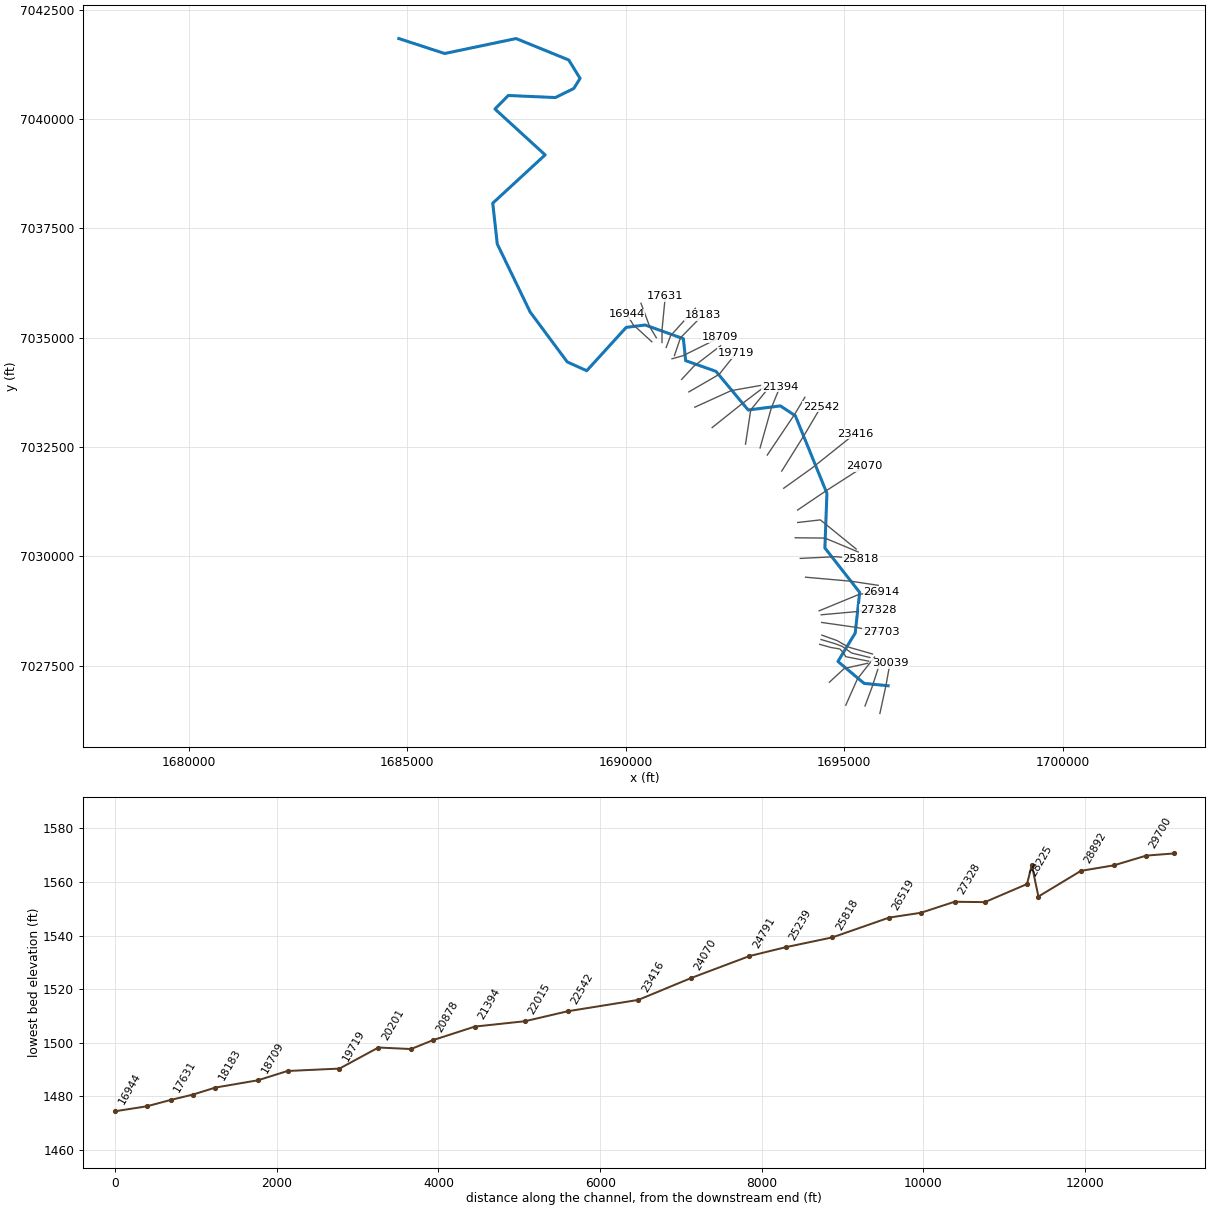
--- Chimney Creek 1190.prj (project) ---

Proj Title=Chimney Creek 1190 Base Level Engineering
Current Plan=p01
Default Exp/Contr=0.3,0.1
English Units
Geom File=g01
Flow File=f01
Plan File=p01
Y Axis Title=Elevation
X Axis Title(PF)=Main Channel Distance
X Axis Title(XS)=Station
BEGIN DESCRIPTION:
Chimney Creek 1190
END DESCRIPTION:
DSS Export Rating Curves= 0
DSS Export Rating Curve Sorted= 0
DSS Export Volume Flow Curves= 0
DXF OffsetX= 0
DXF OffsetY= 0
DXF ScaleX= 1
DXF ScaleY= 10

--- Chimney Creek 1190.p01 (plan) ---

Plan Title=Multiple Run
Short Identifier=Multiple
Geom File=g01
Flow File=f01
Subcritical Flow
K Sum by GR= 0
Std Step Tol= 0.01
Critical Tol= 0.01
Num of Std Step Trials= 20
Max Error Tol= 0.3
Flow Tol Ratio= 0.001
Split Flow NTrial= 30
Split Flow Tol= 0.02
Split Flow Ratio= 0.02
Log Output Level= 0
Friction Slope Method= 1
Unsteady Friction Slope Method= 2
Unsteady Bridges Friction Slope Method= 1
Parabolic Critical Depth
Global Vel Dist=  1 , 1 , 1
Global Log Level= 0
CheckData=True
Encroach Param= -1, 0, 0, 0
BEGIN DESCRIPTION:
Multiple Run
END DESCRIPTION:

--- Chimney Creek 1190.f01 (steady flow) ---

Flow Title=Multiple
Number of Profiles=7
Profile Names=10-year,25-year,50-year,1pct_min,100-year,1pct_plu,500-year
River Rch & RM= Chimney Creek 11,Reach-1,30039
     451     646     813     510    1017    2029    1609
River Rch & RM= Chimney Creek 11,Reach-1,24070
     771    1134    1453     925    1846    3684    3019
River Rch & RM= Chimney Creek 11,Reach-1,19719
     890    1316    1691    1080    2154    4299    3543
River Rch & RM= Chimney Creek 11,Reach-1,16590
     989    1467    1891    1210    2414    4817    3986
River Rch & RM= Chimney Creek 11,Reach-1,13578
    1109    1653    2136    1371    2735    5457    4542
River Rch & RM= Chimney Creek 11,Reach-1,11212
    1206    1803    2335    1501    2994    5974    4990
River Rch & RM= Chimney Creek 11,Reach-1,1807
    1688    2558    3344    2168    4326    8631    7332
Boundary for River Rch & Prof#=Chimney Creek 11,Reach-1,1
Up Type=0
Dn Type=3
Dn Slope=0.005
Boundary for River Rch & Prof#=Chimney Creek 11,Reach-1,2
Up Type=0
Dn Type=3
Dn Slope=0.005
Boundary for River Rch & Prof#=Chimney Creek 11,Reach-1,3
Up Type=0
Dn Type=3
Dn Slope=0.005
Boundary for River Rch & Prof#=Chimney Creek 11,Reach-1,4
Up Type=0
Dn Type=3
Dn Slope=0.005
Boundary for River Rch & Prof#=Chimney Creek 11,Reach-1,5
Up Type=0
Dn Type=3
Dn Slope=0.005
Boundary for River Rch & Prof#=Chimney Creek 11,Reach-1,6
Up Type=0
Dn Type=3
Dn Slope=0.005
Boundary for River Rch & Prof#=Chimney Creek 11,Reach-1,7
Up Type=0
Dn Type=3
Dn Slope=0.005

--- Chimney Creek 1190.g01 (geometry) ---

Geom Title=Existing Conditions
Program Version=4.10

River Reach=Chimney Creek 11,Reach-1
Reach XY= 30
        1696005.        7027038.       1695456.5      7027091.62
      1694857.17      7027593.45      1695252.94      7028243.85
      1695354.48      7029172.11      1694558.44      7030189.22
        1694605.        7031438.      1693881.99      7033211.47
      1693539.73      7033437.62      1692802.58      7033343.53
      1692064.68      7034227.24      1691371.64      7034471.29
      1691318.64      7034974.54       1690444.5      7035286.78
      1690010.25      7035232.56       1689106.5      7034241.47
      1688660.17      7034443.41      1687810.54      7035585.58
      1687058.81      7037139.56      1686955.38      7038072.84
      1688154.47      7039177.31      1687005.54      7040226.91
      1687310.93      7040535.76      1688389.79      7040488.51
      1688811.07      7040696.13      1688954.26      7040927.31
      1688694.48      7041347.79      1687489.78      7041837.48
      1685855.01      7041495.53        1684805.        7041838.

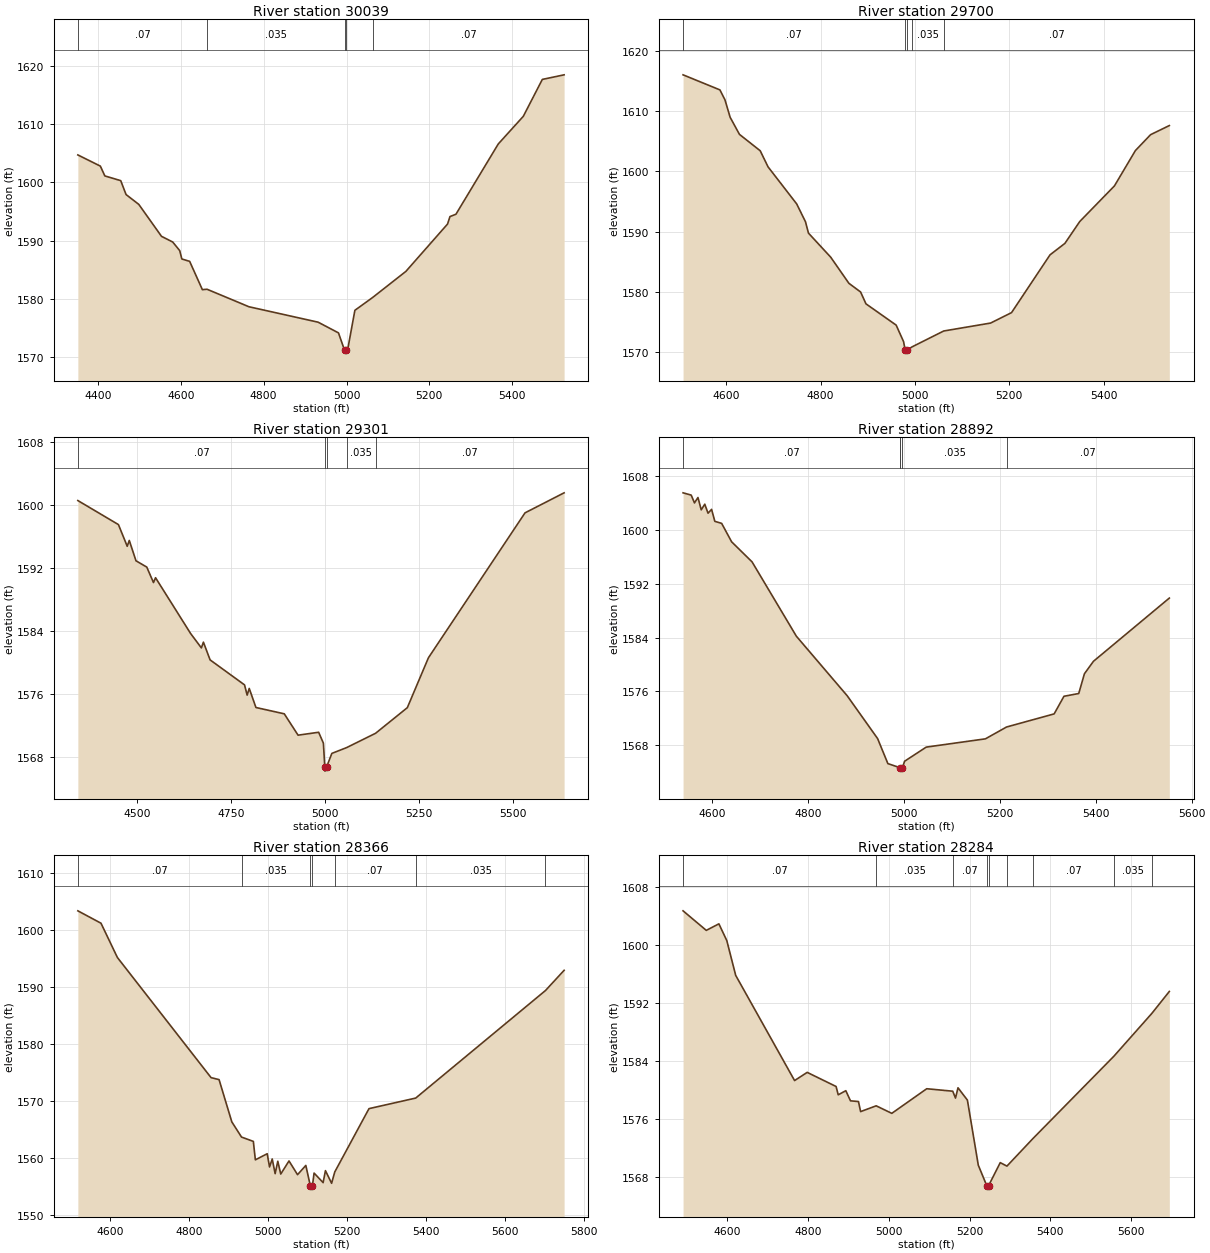
Type RM Length L Ch R = 1 ,30039   ,339,339,339
BEGIN DESCRIPTION:
Chimney Creek 1190 64.0
END DESCRIPTION:
XS GIS Cut Line= 3
      1695817.55      7026404.24      1695954.95      7027038.11
      1696049.44      7027554.85
#Sta/Elev= 30
  4351.4 1604.72  4405.7  1602.8  4416.6 1601.11  4454.9  1600.3  4467.8 1597.91
  4498.5 1596.22  4553.3 1590.73  4580.4 1589.75  4597.3 1588.27  4602.5 1586.83
  4621.3 1586.43    4652 1581.56  4663.3 1581.63  4764.5 1578.62  4931.4 1575.97
  4980.6 1574.13  4995.2 1571.15  4995.5 1570.65  4999.5 1571.15  5002.5 1571.15
  5020.2 1578.01  5062.8  1580.2  5143.3  1584.7  5243.9 1592.84  5249.7 1594.12
  5264.2 1594.53  5366.3  1606.6  5426.8 1611.36  5472.7  1617.7  5525.3 1618.49
#Mann= 5 ,-1 , 0
  4351.4     .07       0  4663.3    .035       0  4995.2    .035       0
  4999.5    .035       0  5062.8     .07       0
Bank Sta=4995.2,4999.5
XS Rating Curve= 0 ,0
Exp/Cntr=0.3,0.1

Type RM Length L Ch R = 1 ,29700   ,399,399,399
BEGIN DESCRIPTION:
Mapping XS cd57d51a
END DESCRIPTION:
XS GIS Cut Line= 3
      1695476.85      7026574.84      1695648.72      7027035.77
      1695812.77      7027548.75
#Sta/Elev= 30
  4508.5 1616.03  4586.6 1613.53  4597.3 1611.88  4608.3 1608.98    4628 1606.15
    4672 1603.43  4688.6 1600.76  4749.3 1594.61    4768 1591.64  4774.2 1589.77
  4821.4 1585.77  4859.9 1581.44  4884.8 1579.99  4896.1 1578.03  4960.1  1574.5
  4975.8 1571.76  4979.3 1570.35  4979.6 1569.85  4983.6 1570.35  4993.6 1570.88
  5060.8 1573.52  5160.3 1574.84  5204.6 1576.57  5286.2 1586.16  5317.7 1588.06
  5349.2 1591.69  5422.7  1597.6  5467.1 1603.46  5499.3  1606.1    5539 1607.61
#Mann= 5 ,-1 , 0
  4508.5     .07       0  4979.3    .035       0  4983.6     .07       0
  4993.6    .035       0  5060.8     .07       0
Bank Sta=4979.3,4983.6
XS Rating Curve= 0 ,0
Exp/Cntr=0.3,0.1

Type RM Length L Ch R = 1 ,29301   ,409,409,409
BEGIN DESCRIPTION:
Mapping XS c401aeab
END DESCRIPTION:
XS GIS Cut Line= 3
      1695036.75      7026593.09      1695304.97      7027197.22
      1695694.95       7027693.8
#Sta/Elev= 30
    4343 1600.55  4450.9  1597.5  4474.2 1594.75  4479.7 1595.49  4497.5 1592.91
  4526.2 1592.11    4544 1590.15  4549.5 1590.76  4642.5  1583.7  4671.3 1581.86
  4676.7 1582.59  4694.5 1580.34    4786 1577.17    4793 1575.87  4798.5 1576.72
  4816.3  1574.3  4891.6  1573.5  4928.3 1570.79    4983 1571.16  4995.6 1569.78
  4999.4 1566.73  4999.7 1566.23  5003.9 1566.73  5018.1 1568.48  5057.2 1569.21
  5134.3 1571.03  5218.7 1574.28  5274.8 1580.61  5531.5 1598.99  5635.4 1601.53
#Mann= 5 ,-1 , 0
    4343     .07       0  4999.4     .07       0  5003.9     .07       0
  5057.2    .035       0  5134.3     .07       0
Bank Sta=4999.4,5003.9
XS Rating Curve= 0 ,0
Exp/Cntr=0.3,0.1

Type RM Length L Ch R = 1 ,28892   ,526,526,526
BEGIN DESCRIPTION:
Mapping XS c41edf8d
END DESCRIPTION:
XS GIS Cut Line= 3
      1694661.09      7027118.22      1695001.35      7027432.44
      1695539.53      7027552.23
#Sta/Elev= 30
  4538.9 1605.54  4555.9  1605.2  4562.7 1604.04    4570 1604.84  4576.8 1603.01
  4584.2 1603.85    4591 1602.51  4598.4 1603.08  4605.2  1601.3  4619.4    1601
  4640.3 1598.25  4682.9 1595.27  4775.3 1584.22  4881.3 1575.37  4944.8    1569
  4966.2 1565.28  4991.8 1564.66  4991.9 1564.66  4992.2 1564.16  4996.5 1564.66
  5001.1 1565.63  5046.2 1567.73  5169.7 1568.96  5213.8 1570.72  5313.1 1572.67
  5333.6 1575.29  5364.4  1575.7  5376.3 1578.64  5395.1 1580.49  5553.4 1589.89
#Mann= 5 ,-1 , 0
  4538.9     .07       0  4991.8    .035       0  4991.9    .035       0
  4996.5    .035       0  5213.8     .07       0
Bank Sta=4991.9,4996.5
XS Rating Curve= 0 ,0
Exp/Cntr=0.3,0.1

Type RM Length L Ch R = 1 ,28366   ,82,82,82
BEGIN DESCRIPTION:
Mapping XS e853631e
END DESCRIPTION:
XS GIS Cut Line= 6
      1694438.54      7027985.27      1694691.98      7027914.09
      1694902.05      7027877.64      1694992.32      7027778.68
      1695037.46      7027702.29      1695559.98      7027599.87
#Sta/Elev= 30
  4518.2 1603.33  4576.8 1601.16  4618.4 1595.15  4855.6 1574.11  4875.9 1573.76
  4908.1 1566.37  4932.7  1563.7  4962.7 1562.94  4967.8 1559.71  4997.8 1560.78
  5003.7 1558.46  5010.5 1559.86  5017.9 1557.29  5024.6 1559.47  5032.1 1557.22
    5053 1559.52  5074.6 1557.11  5095.6 1558.73  5107.3 1555.08  5107.7 1554.58
  5112.2 1555.08  5116.5 1557.39  5139.4 1555.72  5145.3 1557.82  5160.9  1555.6
  5168.9 1557.59  5255.6 1568.68  5373.9 1570.53  5702.6 1589.37  5749.8 1592.91
#Mann= 7 ,-1 , 0
  4518.2     .07       0  4932.7    .035       0  5107.3    .035       0
  5112.2    .035       0  5168.9     .07       0  5373.9    .035       0
  5702.6     .07       0
Bank Sta=5107.3,5112.2
XS Rating Curve= 0 ,0
Exp/Cntr=0.3,0.1

Type RM Length L Ch R = 1 ,28284   ,59,59,59
BEGIN DESCRIPTION:
Mapping XS c079c2d0
END DESCRIPTION:
XS GIS Cut Line= 6
      1694469.77      7028094.64      1694777.05      7028004.37
      1694950.66      7027940.14      1695049.62      7027872.43
      1695167.67      7027787.36      1695589.51       7027683.2
#Sta/Elev= 30
    4490 1604.76  4547.6 1602.06  4578.8 1602.96  4598.4 1600.65  4620.5 1595.84
  4766.4 1581.31  4797.7 1582.44  4869.3 1580.49  4874.6 1579.34  4893.4 1579.91
    4905 1578.51  4924.8 1578.41  4930.1 1577.02  4968.7 1577.82  5007.4 1576.78
    5094 1580.18  5158.4 1579.84  5165.3 1578.89  5171.5 1580.31  5194.8 1578.61
  5221.8 1569.62  5242.6 1566.81    5243 1566.31  5247.5 1566.81  5276.2 1569.97
  5292.8 1569.49  5357.8 1573.33  5558.2 1584.69    5652 1590.59  5695.3 1593.62
#Mann= 9 ,-1 , 0
    4490     .07       0  4968.7    .035       0  5158.4     .07       0
  5242.6    .035       0  5247.5     .07       0  5292.8    .035       0
  5357.8     .07       0  5558.2    .035       0    5652     .07       0
Bank Sta=5242.6,5247.5
XS Rating Curve= 0 ,0
Exp/Cntr=0.3,0.1

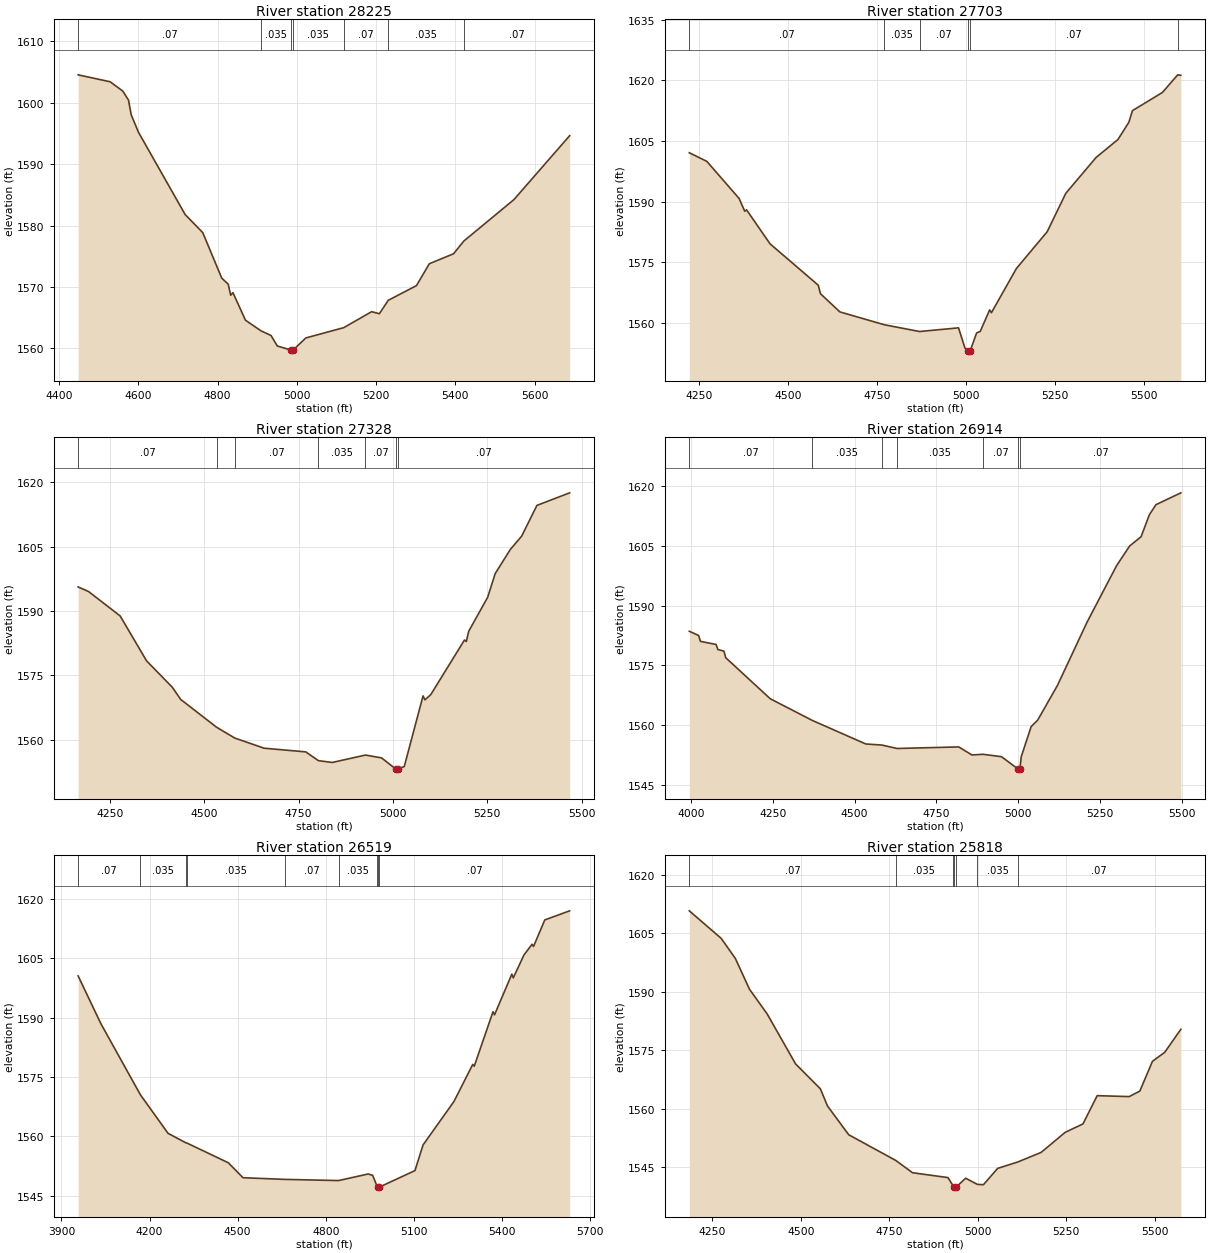
Type RM Length L Ch R = 1 ,28225   ,522,522,522
BEGIN DESCRIPTION:
Mapping XS 1f4bacf5
END DESCRIPTION:
XS GIS Cut Line= 5
      1694488.82      7028195.36      1694837.81      7028070.34
      1694994.06      7027980.07      1695117.32      7027915.83
      1695646.84      7027764.79
#Sta/Elev= 30
  4447.7 1604.56  4528.6 1603.43  4560.5 1601.91  4574.9 1600.44  4581.7 1598.05
  4600.3 1595.18    4718  1581.8  4762.3 1578.87  4810.3 1571.45  4826.7 1570.46
  4832.8 1568.67  4838.6 1569.08  4870.1 1564.61  4909.1 1562.88  4934.7 1562.11
  4950.5  1560.4  4985.4 1559.74  4985.7 1559.24  4990.3 1559.74  5022.5 1561.71
  5118.3 1563.39  5188.6 1565.99  5208.2 1565.66  5230.6 1567.84  5301.8 1570.23
  5334.3  1573.8  5395.4 1575.42  5421.5  1577.5  5547.7 1584.23  5688.5 1594.65
#Mann= 7 ,-1 , 0
  4447.7     .07       0  4909.1    .035       0  4985.4    .035       0
  4990.3    .035       0  5118.3     .07       0  5230.6    .035       0
  5421.5     .07       0
Bank Sta=4985.4,4990.3
XS Rating Curve= 0 ,0
Exp/Cntr=0.3,0.1

Type RM Length L Ch R = 1 ,27703   ,375,375,375
BEGIN DESCRIPTION:
Mapping XS 87e8990c
END DESCRIPTION:
XS GIS Cut Line= 3
      1694486.29      7028484.99       1695255.4      7028375.61
      1695848.53      7028262.88
#Sta/Elev= 30
  4222.6  1602.1  4271.8 1599.97  4362.7 1590.76  4378.3 1587.61  4383.4 1587.97
  4449.2 1579.57  4584.9  1569.3  4590.9 1567.21  4645.5  1562.7  4770.1 1559.52
  4869.4 1557.84  4978.8 1558.75  4996.7 1553.78  5006.3 1552.99  5006.7 1552.49
  5011.3 1552.99  5029.6 1557.49  5039.8 1557.87  5066.1 1563.17  5071.2  1562.5
  5141.5 1573.46  5227.9 1582.55  5280.1 1592.06  5365.5 1600.96  5426.6 1605.38
  5457.1 1609.62  5467.3 1612.52  5551.4 1617.02  5594.4 1621.39  5603.2 1621.27
#Mann= 6 ,-1 , 0
  4222.6     .07       0  4770.1    .035       0  4869.4     .07       0
  5006.3     .07       0  5011.3     .07       0  5594.4    .035       0
Bank Sta=5006.3,5011.3
XS Rating Curve= 0 ,0
Exp/Cntr=0.3,0.1

Type RM Length L Ch R = 1 ,27328   ,414,414,414
BEGIN DESCRIPTION:
Mapping XS 016a154f
END DESCRIPTION:
XS GIS Cut Line= 3
      1694474.18      7028660.33      1695302.28      7028734.99
      1695771.43      7028778.26
#Sta/Elev= 30
  4165.8  1595.6  4193.6 1594.52  4277.1 1588.84  4347.4 1578.33  4415.4  1572.2
  4437.7 1569.35  4532.9 1562.86  4580.9 1560.35  4658.6 1557.98  4769.1 1557.12
  4802.6 1555.07  4839.3 1554.65  4927.3 1556.38  4969.9 1555.72  5007.5 1553.13
  5007.9 1552.63  5012.5 1553.13  5030.1  1553.7  5079.9 1570.19  5084.9 1569.26
  5100.4 1570.48  5189.6 1583.21  5194.6 1582.86  5200.8 1585.24  5251.1 1593.18
  5271.1 1598.71  5311.3 1604.35  5341.4 1607.47  5381.6 1614.61  5468.4 1617.55
#Mann= 7 ,-1 , 0
  4165.8     .07       0  4532.9    .035       0  4580.9     .07       0
  4802.6    .035       0  4927.3     .07       0  5007.5     .07       0
  5012.5     .07       0
Bank Sta=5007.5,5012.5
XS Rating Curve= 0 ,0
Exp/Cntr=0.3,0.1

Type RM Length L Ch R = 1 ,26914   ,395,395,395
BEGIN DESCRIPTION:
Mapping XS 11028446
END DESCRIPTION:
XS GIS Cut Line= 3
      1694426.43      7028750.97      1695355.23       7029132.9
      1695850.87      7029172.76
#Sta/Elev= 30
    3995 1583.55  4023.6 1582.49    4029 1581.03  4076.9 1580.25  4082.3 1578.97
  4100.8 1578.58  4106.3 1576.93  4242.3 1566.65  4370.9 1561.22  4534.1 1555.33
  4583.2 1555.06  4629.7  1554.2    4818 1554.59  4858.5 1552.57  4891.5 1552.75
  4948.6 1552.15  4999.7 1549.03  5000.1 1548.53  5004.8 1549.03  5009.1 1552.17
  5039.2 1559.67  5059.2  1561.3  5119.4 1569.96  5209.7 1585.77    5300 1599.95
  5340.1 1604.91    5375 1607.22  5400.3 1612.72  5420.4 1615.24  5496.5 1618.22
#Mann= 7 ,-1 , 0
    3995     .07       0  4370.9    .035       0  4583.2     .07       0
  4629.7    .035       0  4891.5     .07       0  4999.7     .07       0
  5004.8     .07       0
Bank Sta=4999.7,5004.8
XS Rating Curve= 0 ,0
Exp/Cntr=0.3,0.1

Type RM Length L Ch R = 1 ,26519   ,701,701,701
BEGIN DESCRIPTION:
Mapping XS 163a84b5
END DESCRIPTION:
XS GIS Cut Line= 3
      1694115.61      7029520.06      1695155.58      7029428.04
      1695778.84      7029334.29
#Sta/Elev= 30
  3956.7 1600.52  4034.1 1588.48  4168.8 1570.53    4263  1560.8    4323 1558.43
  4328.1 1558.32  4468.1 1553.38  4518.3  1549.6  4659.7 1549.18  4843.9 1548.88
  4944.7 1550.54    4960  1550.2  4973.4 1547.72  4977.5 1547.22  4977.9 1546.72
  4982.6 1547.22  5104.1  1551.4  5131.6 1557.86    5237 1568.84    5301 1578.19
  5306.1 1577.74    5370 1591.49  5375.1 1590.69    5434 1600.95    5439 1600.02
  5475.4  1605.8    5503  1608.5    5508 1607.93  5546.2 1614.63    5631 1616.93
#Mann= 9 ,-1 , 0
  3956.7     .07       0  4168.8    .035       0    4323     .07       0
  4328.1    .035       0  4659.7     .07       0  4843.9    .035       0
  4973.4     .07       0  4977.5     .07       0  4982.6     .07       0
Bank Sta=4977.5,4982.6
XS Rating Curve= 0 ,0
Exp/Cntr=0.3,0.1

Type RM Length L Ch R = 1 ,25818   ,579,579,579
BEGIN DESCRIPTION:
Mapping XS 31c0736b
END DESCRIPTION:
XS GIS Cut Line= 3
      1693995.11      7029949.33      1694812.87      7029989.27
      1695380.29      7029935.47
#Sta/Elev= 30
  4184.9 1610.77  4274.9 1603.71  4314.9 1598.57    4355 1590.64    4405 1584.29
  4485.1 1571.49  4555.2 1565.09  4575.3 1560.68  4635.3  1553.3  4768.6 1546.68
  4815.5 1543.55  4915.7  1542.3  4929.1 1540.35  4932.9 1539.84  4933.3 1539.34
  4938.4 1539.84  4965.7 1542.14  4998.7 1540.56  5015.8 1540.47    5056 1544.66
  5112.8  1546.3  5178.8 1548.76  5246.8 1553.91  5297.1 1556.08  5337.3 1563.33
  5427.7 1563.09  5457.8 1564.51  5493.4 1572.14  5528.1 1574.46  5573.6 1580.36
#Mann= 7 ,-1 , 0
  4184.9     .07       0  4768.6    .035       0  4929.1     .07       0
  4932.9    .035       0  4938.4     .07       0  4998.7    .035       0
  5112.8     .07       0
Bank Sta=4932.9,4938.4
XS Rating Curve= 0 ,0
Exp/Cntr=0.3,0.1

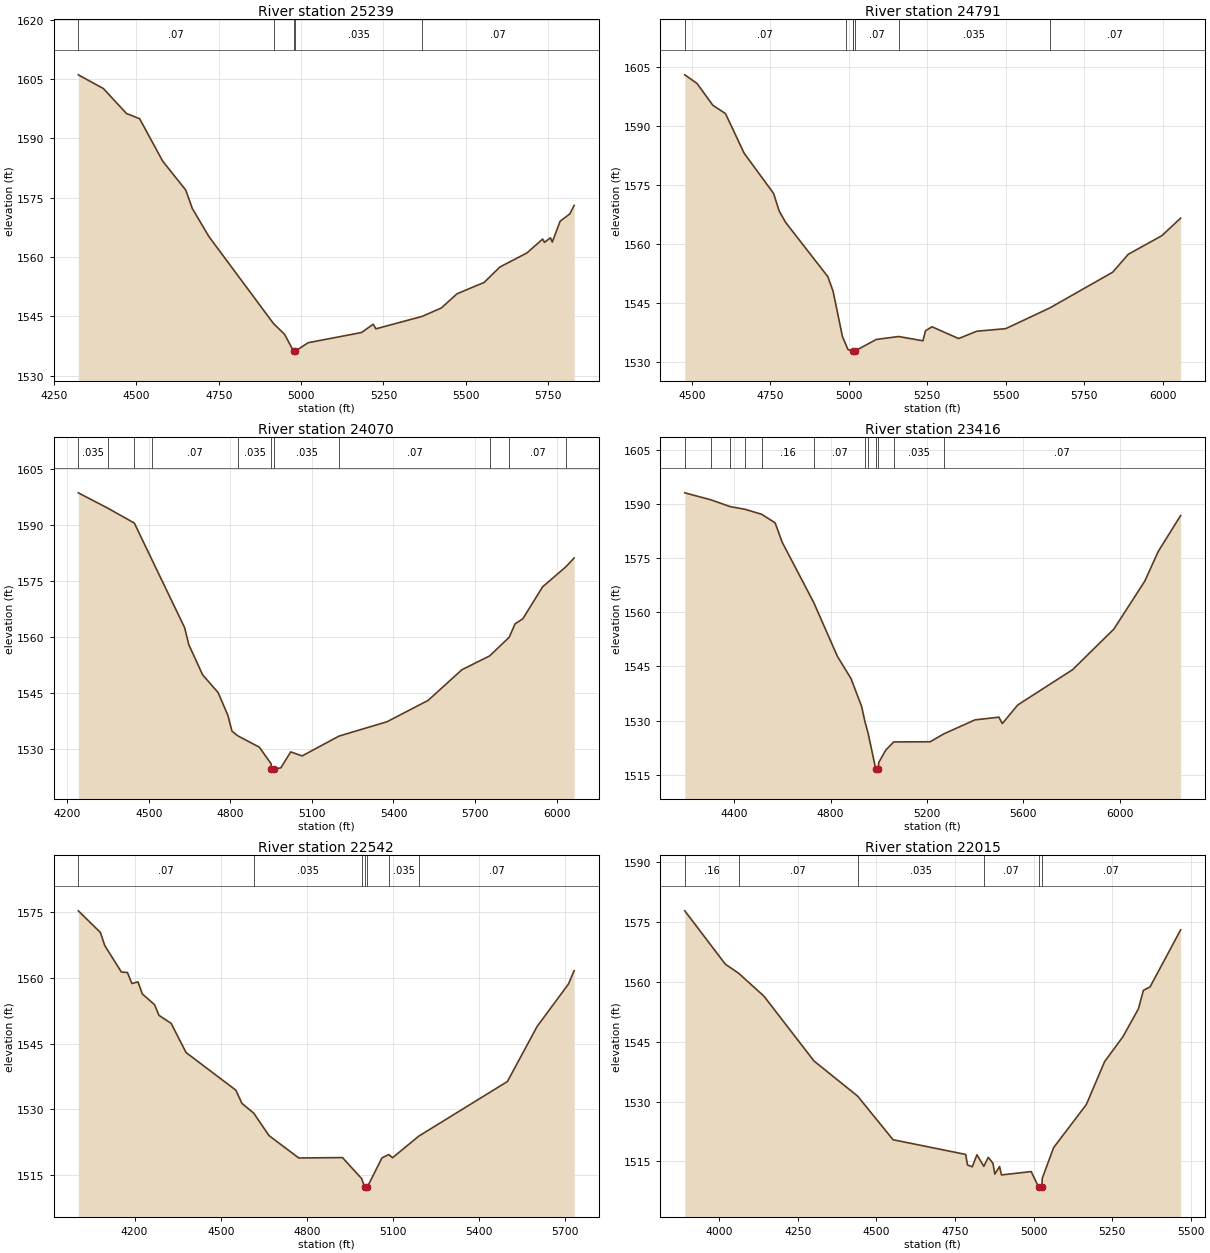
Type RM Length L Ch R = 1 ,25239   ,448,448,448
BEGIN DESCRIPTION:
Mapping XS e36292e3
END DESCRIPTION:
XS GIS Cut Line= 3
      1693878.88      7030421.56       1694559.4      7030414.61
      1695320.74      7030097.24
#Sta/Elev= 30
  4323.6 1606.09  4399.7 1602.62  4469.7 1596.31  4509.7 1594.99  4579.7 1584.25
  4649.7 1576.94  4669.7 1572.28  4719.7 1565.21  4916.4 1543.13  4949.8 1540.43
    4977 1536.17  4977.4 1535.67  4982.6 1536.17  5021.1  1538.3  5183.6 1540.89
  5218.9 1542.99  5226.9 1541.82  5367.3 1544.96  5425.8  1547.1  5473.4 1550.69
  5555.7 1553.56  5603.4 1557.45  5685.7 1561.03  5733.4 1564.53  5738.8  1563.7
  5757.2 1564.85  5762.6 1563.78  5786.5 1569.06  5815.7 1570.89    5829 1573.05
#Mann= 5 ,-1 , 0
  4323.6     .07       0  4916.4    .035       0    4977    .035       0
  4982.6    .035       0  5367.3     .07       0
Bank Sta=4977,4982.6
XS Rating Curve= 0 ,0
Exp/Cntr=0.3,0.1

Type RM Length L Ch R = 1 ,24791   ,721,721,721
BEGIN DESCRIPTION:
Mapping XS 26a74054
END DESCRIPTION:
XS GIS Cut Line= 3
      1693936.25      7030770.87      1694454.45      7030830.76
      1695274.76       7030164.1
#Sta/Elev= 30
  4477.8 1602.93  4516.8 1600.74  4567.1 1595.21  4607.4  1593.1  4666.7 1583.07
  4760.6 1572.85  4778.5 1568.36  4798.7 1565.53  4933.2 1551.76  4949.7 1548.14
  4979.9 1536.52  4990.3 1534.62  4997.2 1533.29  5011.9 1532.89  5012.8 1532.87
  5013.3 1532.37  5018.5 1532.87  5087.5 1535.84  5158.4 1536.58  5236.1  1535.5
  5244.1 1538.03  5264.9 1539.05  5349.6 1536.06  5407.1 1537.92  5499.8 1538.58
  5640.5 1543.85  5840.2 1552.89  5889.8 1557.43  5996.8 1562.15  6056.5  1566.6
#Mann= 7 ,-1 , 0
  4477.8     .07       0  4990.3    .035       0  5011.9     .07       0
  5012.8    .035       0  5018.5     .07       0  5158.4    .035       0
  5640.5     .07       0
Bank Sta=5012.8,5018.5
XS Rating Curve= 0 ,0
Exp/Cntr=0.3,0.1

Type RM Length L Ch R = 1 ,24070   ,654,654,654
BEGIN DESCRIPTION:
Mapping XS c28ca578
END DESCRIPTION:
XS GIS Cut Line= 3
      1693933.62      7031055.59      1694565.56      7031482.67
      1695457.94       7032055.6
#Sta/Elev= 30
  4241.3 1598.58  4351.9 1594.39  4447.2  1590.5  4510.8 1580.87  4632.4  1562.5
  4647.4 1558.01  4698.3 1549.93  4755.3 1545.19  4791.2  1539.1  4806.2 1534.88
  4827.4 1533.63  4906.8 1530.59    4950 1526.17  4951.4 1524.68  4951.9 1524.18
  4960.8 1524.68    4986 1525.07  5022.2 1529.32  5064.4 1528.25  5199.9 1533.55
  5376.3 1537.38  5527.5 1543.09  5651.7 1551.29  5753.8 1554.98  5825.8 1559.99
  5847.1 1563.55  5875.7  1564.9  5948.4 1573.44  6034.9 1578.86  6064.5 1581.17
#Mann= 11 ,-1 , 0
  4241.3    .035       0  4351.9     .07       0  4447.2    .035       0
  4510.8     .07       0  4827.4    .035       0  4951.4    .035       0
  4960.8    .035       0  5199.9     .07       0  5753.8    .035       0
  5825.8     .07       0  6034.9     .16       0
Bank Sta=4951.4,4960.8
XS Rating Curve= 0 ,0
Exp/Cntr=0.3,0.1

Type RM Length L Ch R = 1 ,23416   ,874,874,874
BEGIN DESCRIPTION:
Mapping XS 5105cfab
END DESCRIPTION:
XS GIS Cut Line= 3
      1693616.22      7031554.17       1694272.5      7032022.95
      1695250.06      7032802.91
#Sta/Elev= 30
  4195.2 1593.09  4304.2 1591.14  4383.1 1589.28  4444.5 1588.54  4514.2 1587.15
  4570.1 1584.76  4599.2 1579.41  4730.3 1562.69  4828.2 1547.82  4884.7 1541.65
  4928.9 1533.92  4942.7 1529.68  4955.6 1526.56  4987.7 1516.51  4988.2 1516.01
  4997.2 1516.51  5000.2 1518.45    5029 1521.84  5062.2  1524.1  5213.1 1524.14
  5270.2 1526.34  5398.9  1530.2  5498.1 1530.96  5512.6 1529.18  5576.6 1534.34
    5804  1544.1  5975.3 1555.35  6103.4 1568.61  6159.5 1576.86  6252.3  1586.8
#Mann= 12 ,-1 , 0
  4195.2    .035       0  4304.2     .07       0  4383.1    .035       0
  4444.5     .07       0  4514.2     .16       0  4730.3     .07       0
  4942.7    .035       0  4955.6     .07       0  4987.7     .07       0
  4997.2     .07       0  5062.2    .035       0  5270.2     .07       0
Bank Sta=4987.7,4997.2
XS Rating Curve= 0 ,0
Exp/Cntr=0.3,0.1

Type RM Length L Ch R = 1 ,22542   ,527,527,527
BEGIN DESCRIPTION:
Mapping XS b706100a
END DESCRIPTION:
XS GIS Cut Line= 3
      1693570.24      7031946.34       1694101.5       7032795.3
      1694470.63       7033419.2
#Sta/Elev= 30
    4004 1575.29  4080.8 1570.36  4096.1 1567.36  4153.9 1561.32  4175.1  1561.2
  4190.4  1558.7  4211.7 1559.07    4227 1556.31  4269.4 1553.87  4284.7 1551.44
  4327.2  1549.6  4379.1 1542.95  4552.4 1534.36  4573.6 1531.34  4614.8 1529.11
  4667.9 1523.99  4771.6 1518.88  4923.7 1518.97  4990.6 1514.16  5000.6 1512.27
  5001.1 1511.77  5010.4 1512.27  5061.2  1518.9  5084.8 1519.66  5098.2 1518.94
  5189.3 1523.86    5498 1536.33  5601.2 1548.87  5710.5 1558.58  5730.4 1561.63
#Mann= 7 ,-1 , 0
    4004     .07       0  4614.8    .035       0  4990.6     .07       0
  5000.6     .07       0  5010.4     .07       0  5084.8    .035       0
  5189.3     .07       0
Bank Sta=5000.6,5010.4
XS Rating Curve= 0 ,0
Exp/Cntr=0.3,0.1

Type RM Length L Ch R = 1 ,22015   ,621,621,621
BEGIN DESCRIPTION:
Mapping XS 5a7e6fba
END DESCRIPTION:
XS GIS Cut Line= 3
      1693239.54      7032313.57      1693861.91      7033238.01
      1694100.75      7033635.21
#Sta/Elev= 30
  3890.3 1577.82  4019.3 1564.45  4061.7 1562.17  4142.3 1556.42  4301.2  1540.2
  4440.4 1531.37  4553.1 1520.44  4784.1 1516.76  4790.1 1514.11  4805.1 1513.65
    4820 1516.67  4841.9 1513.77    4856 1516.03    4871 1514.55    4877 1511.82
    4892 1513.72  4898.1 1511.62  4992.7 1512.46  5016.4 1508.56  5016.9 1508.06
  5026.3 1508.56    5028 1510.79  5064.1 1518.48  5168.1 1529.26  5226.4 1540.04
  5284.8 1546.29  5334.1 1553.29  5349.6 1557.87    5371 1558.76  5468.2 1573.04
#Mann= 6 ,-1 , 0
  3890.3     .16       0  4061.7     .07       0  4440.4    .035       0
  4841.9     .07       0  5016.4     .07       0  5026.3     .07       0
Bank Sta=5016.4,5026.3
XS Rating Curve= 0 ,0
Exp/Cntr=0.3,0.1

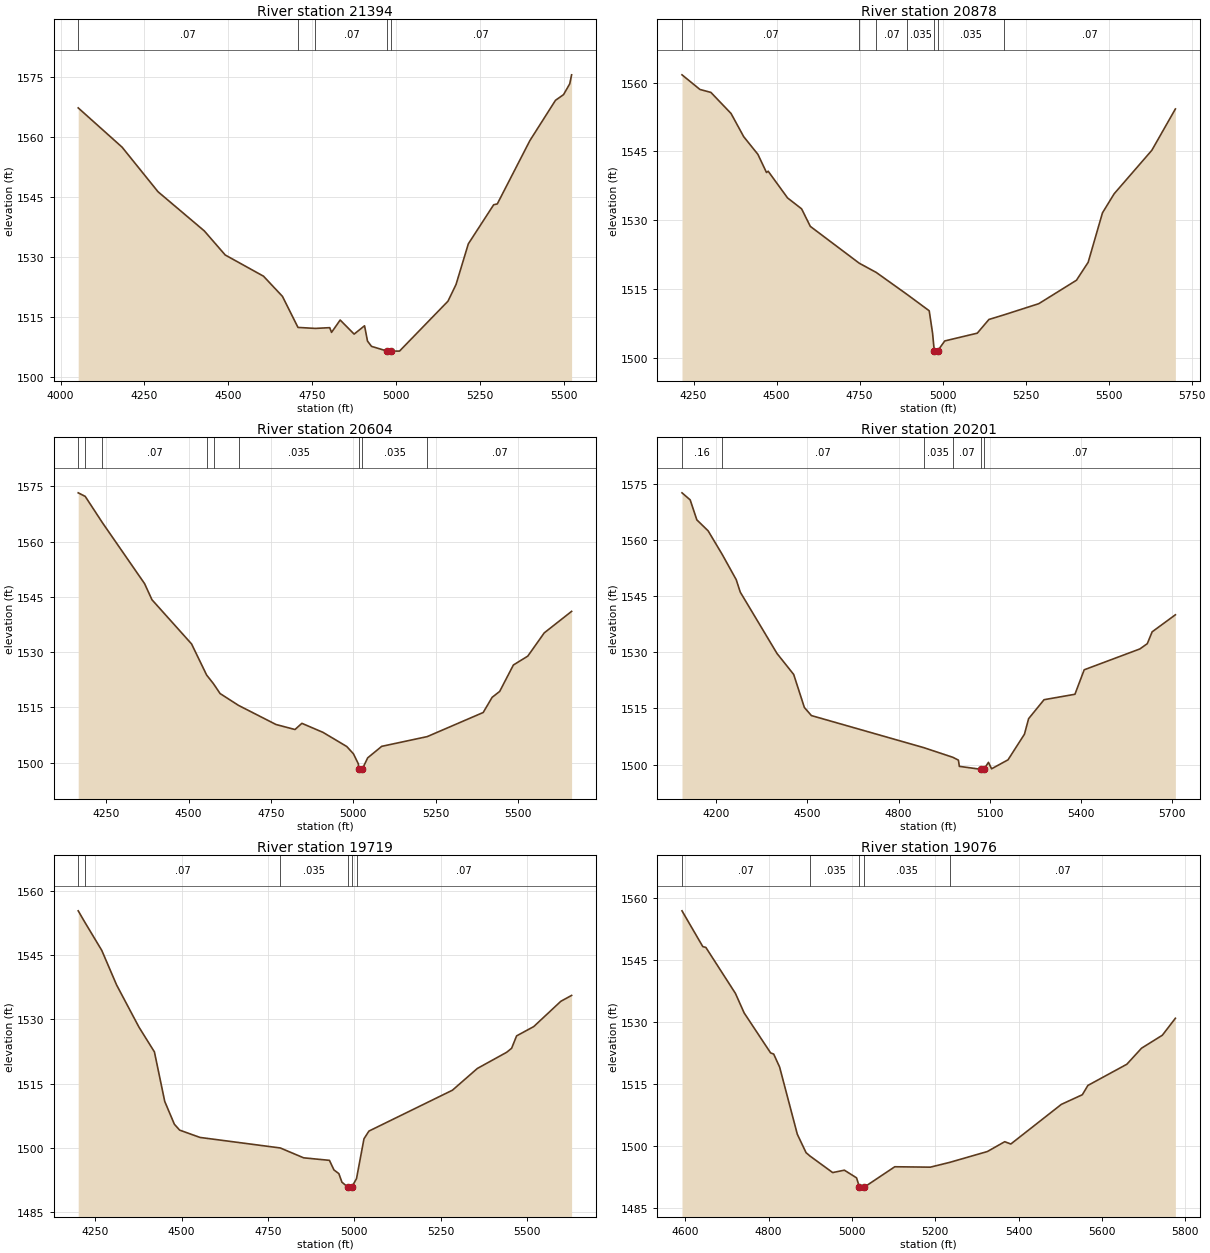
Type RM Length L Ch R = 1 ,21394   ,516,516,516
BEGIN DESCRIPTION:
Mapping XS caa7b7ca
END DESCRIPTION:
XS GIS Cut Line= 3
      1693074.79      7032476.04      1693332.62      7033390.14
      1693529.96      7033873.12
#Sta/Elev= 30
  4052.5 1567.39  4183.3 1557.57  4290.5 1546.42  4428.6 1536.62  4490.9  1530.6
  4605.2 1525.29  4661.7 1520.24    4708 1512.48  4759.8 1512.23  4802.6 1512.42
  4808.1 1511.24  4833.8 1514.33  4875.4 1510.81  4906.5 1512.89  4915.3 1509.06
  4927.3 1507.74  4974.3 1506.55  4974.8 1506.05  4984.3 1506.55  5010.8 1506.56
  5155.3 1519.04  5179.3 1523.21    5216 1533.38  5291.6 1543.16  5302.4 1543.37
  5399.6 1559.21  5475.9 1569.28    5500 1570.71  5518.5 1573.42    5524 1575.66
#Mann= 5 ,-1 , 0
  4052.5     .07       0    4708    .035       0  4759.8     .07       0
  4974.3     .07       0  4984.3     .07       0
Bank Sta=4974.3,4984.3
XS Rating Curve= 0 ,0
Exp/Cntr=0.3,0.1

Type RM Length L Ch R = 1 ,20878   ,274,274,274
BEGIN DESCRIPTION:
Mapping XS 767147ab
END DESCRIPTION:
XS GIS Cut Line= 3
      1692741.46      7032561.98      1692861.26      7033345.86
      1693297.98      7033883.96
#Sta/Elev= 30
    4215 1561.69  4269.1  1558.5    4302 1557.86  4362.7 1553.27    4401 1548.19
  4443.6 1544.36  4469.5  1540.4  4474.6 1540.67    4533 1534.85  4575.2 1532.48
  4601.5 1528.65  4748.9 1520.62  4799.9 1518.62    4893 1513.81  4959.6 1510.25
  4969.7 1505.37  4974.8 1501.52  4975.3 1501.02  4984.9 1501.52  5006.5 1503.68
  5104.3 1505.37  5139.5 1508.36  5184.7 1509.36  5289.6  1511.8  5403.1 1516.91
  5438.3 1520.82  5481.4  1531.6  5516.6 1535.76  5630.1 1545.24    5701 1554.25
#Mann= 7 ,-1 , 0
    4215     .07       0  4748.9    .035       0  4799.9     .07       0
    4893    .035       0  4974.8    .035       0  4984.9    .035       0
  5184.7     .07       0
Bank Sta=4974.8,4984.9
XS Rating Curve= 0 ,0
Exp/Cntr=0.3,0.1

Type RM Length L Ch R = 1 ,20604   ,403,403,403
BEGIN DESCRIPTION:
Mapping XS 933eed64
END DESCRIPTION:
XS GIS Cut Line= 3
      1691977.68      7032941.38       1692630.9      7033462.22
      1693158.23      7033861.52
#Sta/Elev= 30
  4165.3 1573.24  4186.6 1572.27  4238.3 1565.19  4366.6 1548.59  4389.1 1544.21
  4509.2 1532.21    4555 1523.75  4575.8 1521.39  4595.7 1518.74  4651.7 1515.52
  4765.4 1510.33    4823 1508.97  4843.9 1510.65  4907.9  1508.2    4980 1504.36
  5000.2 1502.39  5015.4 1499.61  5016.4 1498.17  5016.9 1497.67  5026.9 1498.17
  5043.5 1501.27  5086.1  1504.4  5224.1 1507.04    5394 1513.59  5421.1 1517.71
    5444 1519.31  5485.6 1526.49  5529.3  1528.9  5579.2 1535.21  5662.2 1541.05
#Mann= 9 ,-1 , 0
  4165.3     .07       0  4186.6     .16       0  4238.3     .07       0
    4555    .035       0  4575.8     .07       0  4651.7    .035       0
  5016.4    .035       0  5026.9    .035       0  5224.1     .07       0
Bank Sta=5016.4,5026.9
XS Rating Curve= 0 ,0
Exp/Cntr=0.3,0.1

Type RM Length L Ch R = 1 ,20201   ,482,482,482
BEGIN DESCRIPTION:
Mapping XS 5218d328
END DESCRIPTION:
XS GIS Cut Line= 3
      1691580.55      7033407.97      1692411.72      7033785.57
      1693110.24      7033909.22
#Sta/Elev= 30
  4088.1 1572.58    4115  1570.7  4136.9 1565.36  4174.1 1562.42  4220.9 1556.05
  4266.4 1549.38  4279.7 1546.06  4400.5 1529.67  4455.4 1524.06  4490.5 1515.24
  4513.6 1513.08  4883.2 1504.51  4978.8 1501.93    4997 1501.18  5000.1 1499.51
  5070.2 1498.74  5070.7 1498.24  5080.7 1498.74  5095.8 1500.58    5106 1498.86
  5160.1 1501.26  5214.1  1508.1  5227.8 1512.25  5278.6 1517.32  5380.1 1518.77
  5410.6 1525.31  5593.4 1530.87    5618 1532.28    5634 1535.45  5710.4    1540
#Mann= 6 ,-1 , 0
  4088.1     .16       0  4220.9     .07       0  4883.2    .035       0
  4978.8     .07       0  5070.2     .07       0  5080.7     .07       0
Bank Sta=5070.2,5080.7
XS Rating Curve= 0 ,0
Exp/Cntr=0.3,0.1

Type RM Length L Ch R = 1 ,19719   ,643,643,643
BEGIN DESCRIPTION:
Mapping XS 6261a4a3
END DESCRIPTION:
XS GIS Cut Line= 3
      1691443.95      7033757.22       1692138.4      7034158.26
      1692528.99       7034647.8
#Sta/Elev= 30
  4200.7 1555.36  4219.5 1552.75  4268.8 1546.14  4311.9 1538.04  4376.6  1528.2
  4421.3 1522.42  4451.2 1510.85  4479.1 1505.53  4494.3 1504.16  4553.2 1502.45
  4785.7 1499.99  4853.2 1497.69  4927.9  1497.1    4941 1494.86  4955.2    1494
  4964.1    1492  4980.8 1490.88  4981.3 1490.38  4992.6 1490.88  5006.3 1492.83
  5027.9 1502.13  5042.2 1503.93    5284 1513.48    5356 1518.55  5440.9 1522.33
  5455.3 1523.27  5469.7 1526.16  5519.3 1528.33  5597.8 1534.24  5628.9 1535.61
#Mann= 6 ,-1 , 0
  4200.7     .16       0  4219.5     .07       0  4785.7    .035       0
  4980.8    .035       0  4992.6    .035       0  5006.3     .07       0
Bank Sta=4980.8,4992.6
XS Rating Curve= 0 ,0
Exp/Cntr=0.3,0.1

Type RM Length L Ch R = 1 ,19076   ,367,367,367
BEGIN DESCRIPTION:
Mapping XS 379f5036
END DESCRIPTION:
XS GIS Cut Line= 3
      1691279.55      7034042.64      1691557.32      7034342.98
      1692172.18      7034814.09
#Sta/Elev= 30
  4592.4  1556.9  4642.3 1548.24  4649.7 1548.03  4720.6  1536.9  4741.5 1532.17
    4805 1522.48  4812.4  1522.2  4826.6 1519.06  4869.1 1502.77  4890.1 1498.31
  4899.3 1497.51  4953.9 1493.49    4982 1494.07  5011.2 1492.21  5018.1 1489.98
  5018.6 1489.48    5030 1489.98  5102.9  1494.9  5188.1  1494.8  5234.3 1495.95
  5325.1 1498.59  5366.7 1500.97  5381.3 1500.41  5502.5 1510.01  5552.9 1512.35
  5566.2  1514.6  5659.6 1519.73  5694.9 1523.62  5744.8 1526.76  5776.1 1530.87
#Mann= 5 ,-1 , 0
  4592.4     .07       0  4899.3    .035       0  5018.1    .035       0
    5030    .035       0  5234.3     .07       0
Bank Sta=5018.1,5030
XS Rating Curve= 0 ,0
Exp/Cntr=0.3,0.1

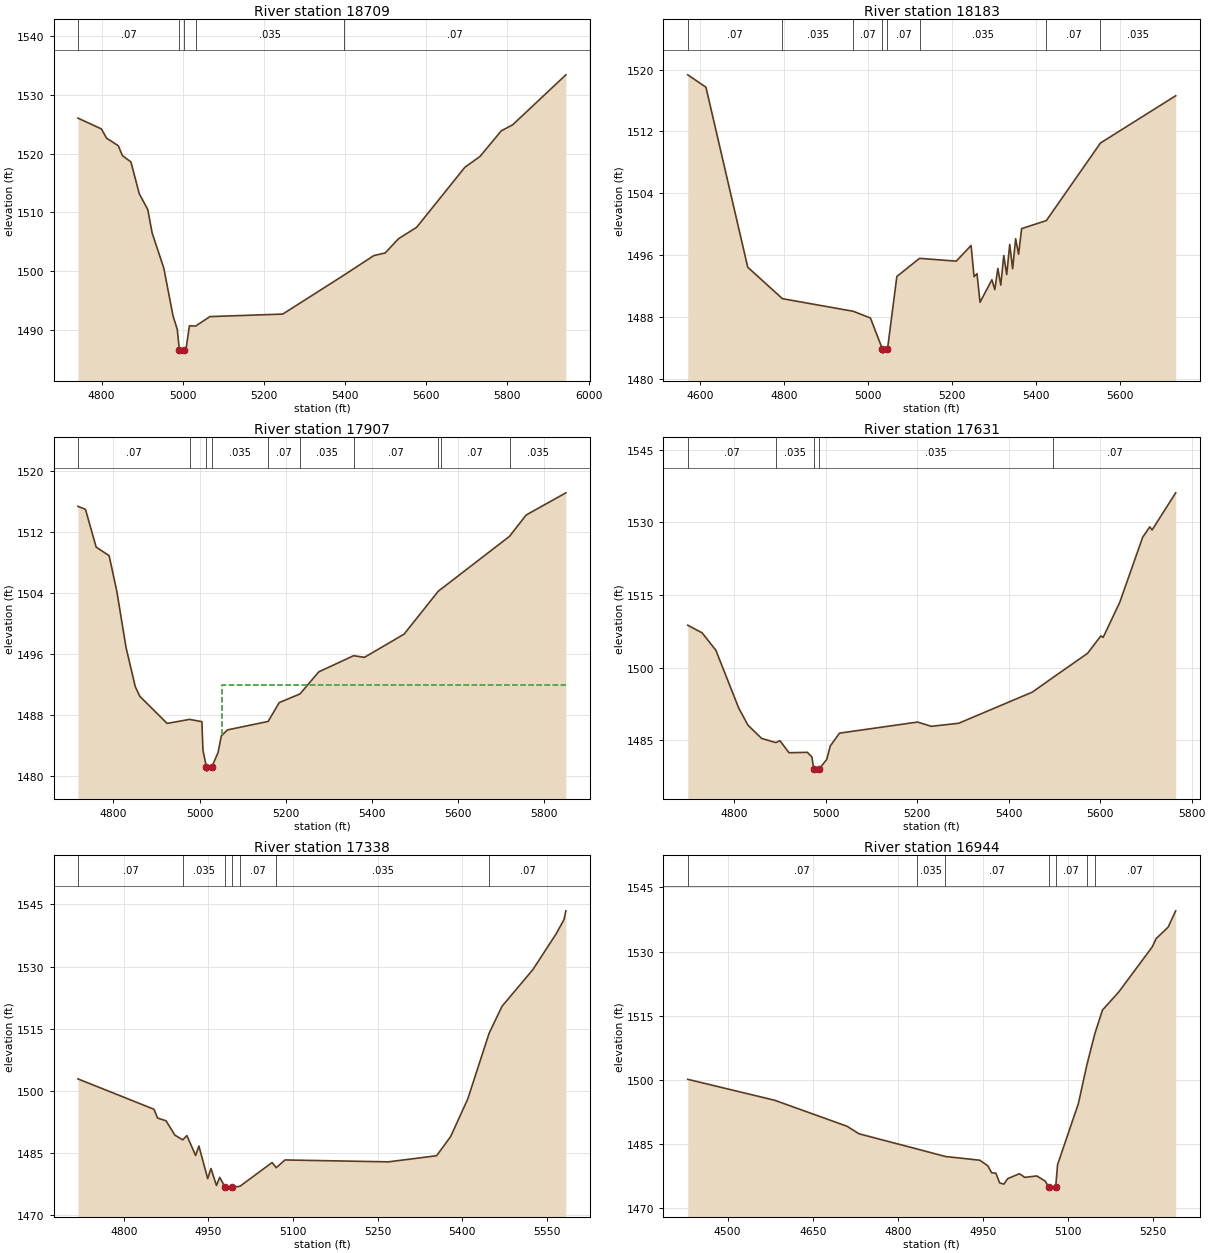
Type RM Length L Ch R = 1 ,18709   ,526,526,526
BEGIN DESCRIPTION:
Mapping XS a3c50c1f
END DESCRIPTION:
XS GIS Cut Line= 3
      1691059.42      7034514.51      1691311.14      7034585.69
      1692154.88      7035002.35
#Sta/Elev= 30
  4741.5 1526.03  4799.3 1524.19  4812.1 1522.61  4840.8 1521.34  4851.3 1519.63
    4872 1518.58  4892.8 1513.13  4913.6 1510.47  4924.4 1506.48  4953.2 1500.47
  4975.9 1492.35  4986.3 1490.06  4991.6 1486.51  4992.1 1486.01  5003.5 1486.51
    5008 1486.77  5016.3 1490.66  5031.5 1490.62  5066.8 1492.23  5246.3 1492.66
  5397.8 1499.32  5470.8 1502.62  5498.8 1503.07  5531.6 1505.49  5576.2 1507.43
  5695.2 1517.66  5732.3 1519.49    5785 1523.87    5813 1524.89  5944.1  1533.4
#Mann= 5 ,-1 , 0
  4741.5     .07       0  4991.6     .07       0  5003.5     .07       0
  5031.5    .035       0  5397.8     .07       0
Bank Sta=4991.6,5003.5
XS Rating Curve= 0 ,0
Exp/Cntr=0.3,0.1

Type RM Length L Ch R = 1 ,18183   ,276,276,276
BEGIN DESCRIPTION:
Mapping XS 1672c78c
END DESCRIPTION:
XS GIS Cut Line= 3
      1691114.17      7034587.05      1691252.74       7034993.9
       1691765.2      7035516.73
#Sta/Elev= 30
  4570.2 1519.32  4613.5 1517.72  4713.1 1494.41  4795.6 1490.34  4964.1 1488.71
  5005.2 1487.84  5033.9 1483.79  5034.4 1483.29  5045.8 1483.79  5068.1 1493.21
  5122.1 1495.56  5209.6  1495.2  5244.9 1497.23    5252 1493.18    5259 1493.58
  5266.2 1489.87  5294.4 1492.79  5301.4 1491.52  5308.6 1494.26  5315.6  1492.1
  5322.7 1495.93  5329.7 1493.46  5336.9 1497.36  5343.9 1494.22    5351  1498.1
    5358 1496.09  5365.2 1499.41  5424.1 1500.45  5552.9 1510.49  5732.1 1516.61
#Mann= 8 ,-1 , 0
  4570.2     .07       0  4795.6    .035       0  4964.1     .07       0
  5033.9     .07       0  5045.8     .07       0  5122.1    .035       0
  5424.1     .07       0  5552.9    .035       0
Bank Sta=5033.9,5045.8
XS Rating Curve= 0 ,0
Exp/Cntr=0.3,0.1

Type RM Length L Ch R = 1 ,17907   ,276,276,276
BEGIN DESCRIPTION:
Mapping XS 4ebde137
END DESCRIPTION:
XS GIS Cut Line= 3
      1690924.96      7034773.59      1691026.97      7035042.72
      1691593.38      7035669.89
#Sta/Elev= 30
  4717.5 1515.38    4735 1514.99  4759.8 1510.04  4789.9 1508.92  4807.8 1504.25
  4829.2 1496.89  4850.6 1491.76  4861.2 1490.49  4924.6 1486.94  4976.8 1487.47
  5005.3 1487.17  5007.8 1483.43  5015.9 1481.19  5016.4 1480.69  5028.1 1481.19
  5042.9 1483.14  5050.4  1485.3  5064.6 1486.09  5159.1  1487.2  5184.9 1489.67
    5233  1490.8  5276.8  1493.7  5357.5 1495.81  5382.9  1495.6  5474.8 1498.64
  5554.3 1504.27  5559.9 1504.51  5719.6 1511.45  5758.1 1514.24  5850.4 1517.15
#Mann= 10 ,-1 , 0
  4717.5     .07       0  4976.8    .035       0  5015.9    .035       0
  5028.1    .035       0  5159.1     .07       0    5233    .035       0
  5357.5     .07       0  5554.3    .035       0  5559.9     .07       0
  5719.6    .035       0
#XS Ineff= 2 , 0
       0                    5052       0    1492
Permanent Ineff=
       F       F
Bank Sta=5015.9,5028.1
XS Rating Curve= 0 ,0
Exp/Cntr=0.3,0.1

Type RM Length L Ch R = 1 ,17631   ,293,293,293
BEGIN DESCRIPTION:
Mapping XS 23766251
END DESCRIPTION:
XS GIS Cut Line= 3
      1690829.49      7034886.47      1690831.66      7035190.29
      1690905.44      7035949.79
#Sta/Elev= 30
  4698.2 1508.77  4729.7 1507.19  4759.7  1503.6  4809.7 1491.68  4829.7 1488.17
  4859.7 1485.43  4890.9 1484.56  4899.7 1484.96  4919.7 1482.47  4959.7 1482.56
  4969.7 1481.59  4973.6 1479.18  4974.1 1478.68  4985.8 1479.18    5002 1481.08
  5009.8 1483.85  5029.9 1486.51  5200.7  1488.8  5230.8 1487.92  5290.6 1488.55
  5451.8 1494.98  5497.9 1498.06  5572.4 1502.97  5601.5 1506.57  5606.5 1506.26
  5642.7 1513.47    5693 1526.93  5708.5 1529.05  5713.5 1528.41  5765.1 1536.07
#Mann= 5 ,-1 , 0
  4698.2     .07       0  4890.9    .035       0  4973.6    .035       0
  4985.8    .035       0  5497.9     .07       0
Bank Sta=4973.6,4985.8
XS Rating Curve= 0 ,0
Exp/Cntr=0.3,0.1

Type RM Length L Ch R = 1 ,17338   ,394,394,394
BEGIN DESCRIPTION:
Mapping XS ff978e13
END DESCRIPTION:
XS GIS Cut Line= 3
      1690699.28      7034997.14      1690551.71      7035242.37
      1690348.08      7035783.94
#Sta/Elev= 30
  4718.9 1502.92  4853.7 1495.59    4860 1493.47  4875.1 1492.81  4890.6 1489.36
  4904.7 1488.21    4912 1489.24  4927.5 1484.44  4933.3 1486.73  4948.9 1478.85
  4954.7  1481.3  4964.4  1477.2  4970.2 1479.17  4979.6 1476.82  4980.1 1476.32
  4991.9 1476.82  5005.9 1476.99    5063 1482.74  5070.4  1481.5  5085.9 1483.36
  5269.3  1482.9  5354.6 1484.38  5379.5 1489.01  5409.8 1498.06  5447.5 1513.87
  5470.5 1520.43  5525.3  1529.3  5566.7 1537.97  5580.5 1541.39  5583.7 1543.47
#Mann= 7 ,-1 , 0
  4718.9     .07       0  4904.7    .035       0  4979.6    .035       0
  4991.9    .035       0  5005.9     .07       0  5070.4    .035       0
  5447.5     .07       0
Bank Sta=4979.6,4991.9
XS Rating Curve= 0 ,0
Exp/Cntr=0.3,0.1

Type RM Length L Ch R = 1 ,16944   ,354,354,354
BEGIN DESCRIPTION:
Mapping XS 53e75054
END DESCRIPTION:
XS GIS Cut Line= 3
       1690597.3      7034903.82      1690171.94      7035292.28
      1690022.24      7035533.09
#Sta/Elev= 30
  4429.9 1500.13  4582.9 1495.24  4710.5 1489.16  4731.5  1487.4  4833.1 1483.87
  4883.8 1482.09  4944.3 1481.22  4958.5 1479.92  4965.2  1478.3  4972.7 1478.18
  4979.4 1475.91  4986.8 1475.63  4993.6 1476.91  5014.1 1478.06  5023.6 1477.21
  5044.8 1477.54  5059.8 1476.33  5065.7 1474.96  5066.2 1474.46  5078.1 1474.96
  5081.4 1480.18    5118 1494.43  5132.9 1503.42  5146.9 1510.72  5160.5 1516.32
  5189.3 1520.56  5248.2 1531.09    5255 1533.02  5276.2 1535.71  5289.5 1539.52
#Mann= 7 ,-1 , 0
  4429.9     .07       0  4833.1    .035       0  4883.8     .07       0
  5065.7     .07       0  5078.1     .07       0  5132.9    .035       0
  5146.9     .07       0
Bank Sta=5065.7,5078.1
XS Rating Curve= 0 ,0
Exp/Cntr=0.3,0.1