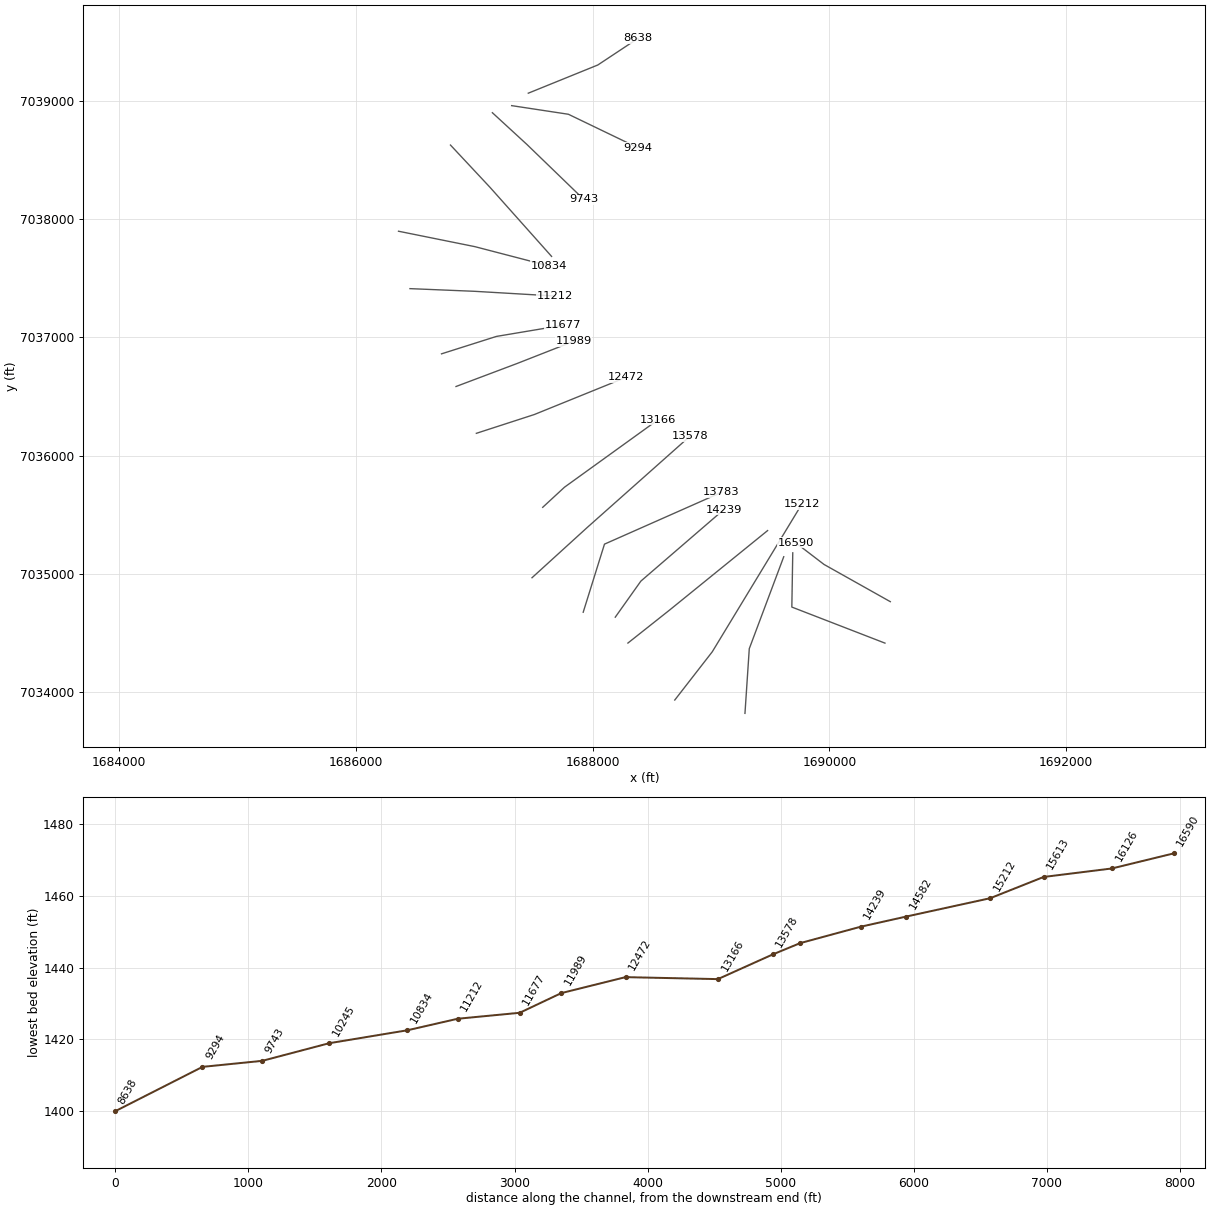
HEC-RAS study Chimney Creek 1190.prj: Chimney Creek 1190 Base Level Engineering

--- Chimney Creek 1190.g01 (geometry) --- (continued)

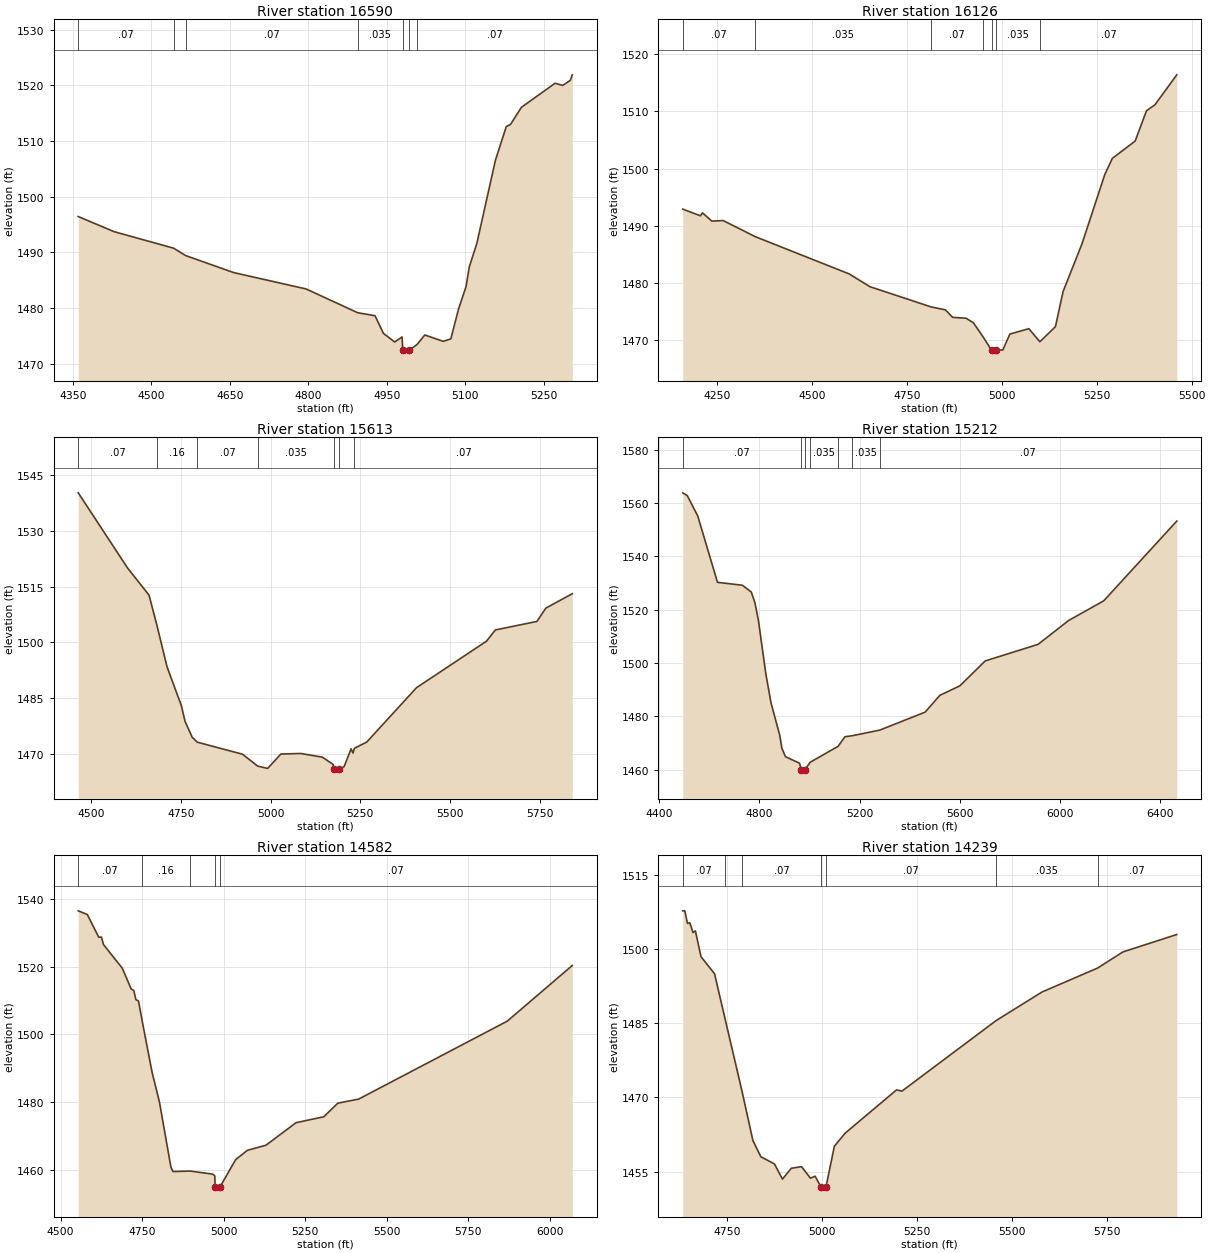
Type RM Length L Ch R = 1 ,16590   ,464,464,464
BEGIN DESCRIPTION:
Mapping XS 4a4e4ced
END DESCRIPTION:
XS GIS Cut Line= 3
      1690514.86      7034764.92      1689954.92      7035079.61
      1689714.76      7035263.52
#Sta/Elev= 30
    4360 1496.42  4428.7  1493.7  4542.2 1490.74  4565.6  1489.4  4657.3 1486.35
  4795.7 1483.41  4894.4 1479.14  4927.6  1478.6  4943.6 1475.43  4965.2 1473.88
  4979.3 1474.79  4980.7 1472.38  4981.2 1471.88  4993.1 1472.38  5008.4 1473.47
  5022.7 1475.14  5058.1    1474  5072.6 1474.44  5087.1 1479.74  5101.6 1483.82
  5107.9 1487.38  5122.4 1491.63  5157.8 1506.53  5178.6 1512.58  5186.8 1512.98
  5207.6 1516.05    5272 1520.37  5286.6 1519.98  5301.1 1520.89  5304.8 1521.88
#Mann= 7 ,-1 , 0
    4360     .07       0  4542.2    .035       0  4565.6     .07       0
  4894.4    .035       0  4980.7    .035       0  4993.1    .035       0
  5008.4     .07       0
Bank Sta=4980.7,4993.1
XS Rating Curve= 0 ,0
Exp/Cntr=0.3,0.1

Type RM Length L Ch R = 1 ,16126   ,513,513,513
BEGIN DESCRIPTION:
Mapping XS 7a317df1
END DESCRIPTION:
XS GIS Cut Line= 3
       1690469.7      7034414.67      1689683.22      7034719.37
      1689691.03      7035177.66
#Sta/Elev= 30
    4159 1492.89  4205.7 1491.72    4211 1492.24  4235.6 1490.79  4265.5 1490.89
  4349.7 1488.08  4597.8 1481.54  4652.3 1479.31  4813.5 1475.77  4851.1 1475.26
  4870.3 1473.94  4905.6 1473.79  4924.8    1473  4949.8 1470.59  4972.8 1468.18
  4973.3 1467.68  4985.3 1468.18  5002.4 1468.23  5021.1 1471.02  5071.1 1471.96
  5100.1 1469.67  5141.1 1472.31  5161.1 1478.43  5211.1 1486.82  5271.1 1498.94
  5291.1 1501.78  5351.1  1504.8  5381.1 1510.12  5403.2 1511.15  5460.8  1516.4
#Mann= 7 ,-1 , 0
    4159     .07       0  4349.7    .035       0  4813.5     .07       0
  4949.8    .035       0  4972.8    .035       0  4985.3    .035       0
  5100.1     .07       0
Bank Sta=4972.8,4985.3
XS Rating Curve= 0 ,0
Exp/Cntr=0.3,0.1

Type RM Length L Ch R = 1 ,15613   ,401,401,401
BEGIN DESCRIPTION:
Mapping XS 10c45de8
END DESCRIPTION:
XS GIS Cut Line= 3
      1689287.39      7033820.93      1689323.84       7034367.8
      1689614.86       7035144.7
#Sta/Elev= 30
  4463.7 1540.31  4601.1 1520.07  4661.2 1512.73  4683.5 1504.46  4711.3 1493.42
  4751.4 1482.93  4761.4 1478.76  4781.5 1474.43  4795.7 1473.11  4921.8 1469.87
    4964 1466.67  4991.9 1466.04  5028.7 1469.91  5083.9 1470.07  5144.4 1469.08
  5174.7 1467.11    5176 1465.81  5176.5 1465.31  5189.7 1465.81    5205 1466.51
  5224.6 1471.32  5229.9 1470.18  5233.8 1471.46  5268.3 1473.15  5407.1  1487.8
  5602.1 1500.32    5627 1503.36  5742.8 1505.65  5767.7 1509.24  5841.4 1513.12
#Mann= 7 ,-1 , 0
  4463.7     .07       0  4683.5     .16       0  4795.7     .07       0
    4964    .035       0    5176    .035       0  5189.7    .035       0
  5233.8     .07       0
Bank Sta=5176,5189.7
XS Rating Curve= 0 ,0
Exp/Cntr=0.3,0.1

Type RM Length L Ch R = 1 ,15212   ,630,630,630
BEGIN DESCRIPTION:
Mapping XS 27388a65
END DESCRIPTION:
XS GIS Cut Line= 3
      1688694.61      7033933.77      1689011.45      7034341.76
      1689766.67      7035587.43
#Sta/Elev= 30
  4493.7 1563.77  4511.7 1562.73  4553.7 1555.08  4632.5  1530.2    4732 1529.11
  4767.3 1526.58  4781.8 1522.66  4796.3 1515.71  4825.2 1496.15  4846.1 1485.07
  4881.4 1472.77  4889.5 1468.03    4904 1464.81  4960.1 1462.37  4967.7 1459.89
  4968.2 1459.39  4981.5 1459.89  5002.9 1462.73  5114.3 1468.69  5141.4 1472.28
  5171.4 1472.68    5281 1474.78    5462 1481.52  5520.4  1487.8  5600.9  1491.4
  5701.8 1500.72  5913.1 1506.94  6035.3  1515.9  6175.3 1523.26    6467 1553.17
#Mann= 7 ,-1 , 0
  4493.7     .07       0  4967.7     .07       0  4981.5     .07       0
  5002.9    .035       0  5114.3     .07       0  5171.4    .035       0
    5281     .07       0
Bank Sta=4967.7,4981.5
XS Rating Curve= 0 ,0
Exp/Cntr=0.3,0.1

Type RM Length L Ch R = 1 ,14582   ,343,343,343
BEGIN DESCRIPTION:
Mapping XS 5ae16c85
END DESCRIPTION:
XS GIS Cut Line= 3
      1688298.88      7034415.23      1688650.41      7034693.85
      1689478.57      7035365.75
#Sta/Elev= 30
    4554 1536.54  4581.8 1535.45    4617 1528.72  4625.1 1528.78  4631.5 1526.56
  4689.2 1519.56  4716.4 1513.44  4724.4 1512.99  4730.8  1510.3  4738.8 1509.89
  4750.2 1503.92  4780.5 1488.79  4802.9 1480.09  4838.2 1460.78  4844.6 1459.48
  4897.7 1459.62  4966.4 1458.71  4972.8 1458.19  4973.9 1454.78  4974.4 1454.28
  4987.8 1454.78  5036.8    1463  5072.9 1465.76  5129.5 1467.25  5222.2 1473.93
  5306.9 1475.66  5350.1 1479.69    5414 1480.89  5869.5 1503.92    6069 1520.38
#Mann= 5 ,-1 , 0
    4554     .07       0  4750.2     .16       0  4897.7     .07       0
  4973.9     .07       0  4987.8     .07       0
Bank Sta=4973.9,4987.8
XS Rating Curve= 0 ,0
Exp/Cntr=0.3,0.1

Type RM Length L Ch R = 1 ,14239   ,456,456,456
BEGIN DESCRIPTION:
Mapping XS f1c62733
END DESCRIPTION:
XS GIS Cut Line= 3
      1688192.08      7034633.96      1688408.22      7034938.64
      1689109.31      7035543.65
#Sta/Elev= 30
  4632.8  1507.7  4638.3  1507.7  4645.2 1505.17  4651.3 1505.29    4660  1503.3
  4666.1 1503.65  4680.9 1498.42  4716.5 1494.98  4744.5 1485.75  4788.5 1471.31
  4817.4 1461.27  4838.3 1457.98    4874 1456.54  4895.2 1453.46  4918.3 1455.65
  4945.3 1455.99  4968.8 1453.65  4981.1 1454.05  4995.9 1451.94  4996.4 1451.44
  5009.8 1451.94  5031.7 1460.12  5060.2 1462.76  5195.2  1471.5  5209.4 1471.25
  5457.3 1485.52    5578 1491.29  5724.4 1496.14  5790.8 1499.39  5932.4 1502.91
#Mann= 7 ,-1 , 0
  4632.8     .07       0  4744.5     .16       0  4788.5     .07       0
  4995.9     .07       0  5009.8     .07       0  5457.3    .035       0
  5724.4     .07       0
Bank Sta=4995.9,5009.8
XS Rating Curve= 0 ,0
Exp/Cntr=0.3,0.1

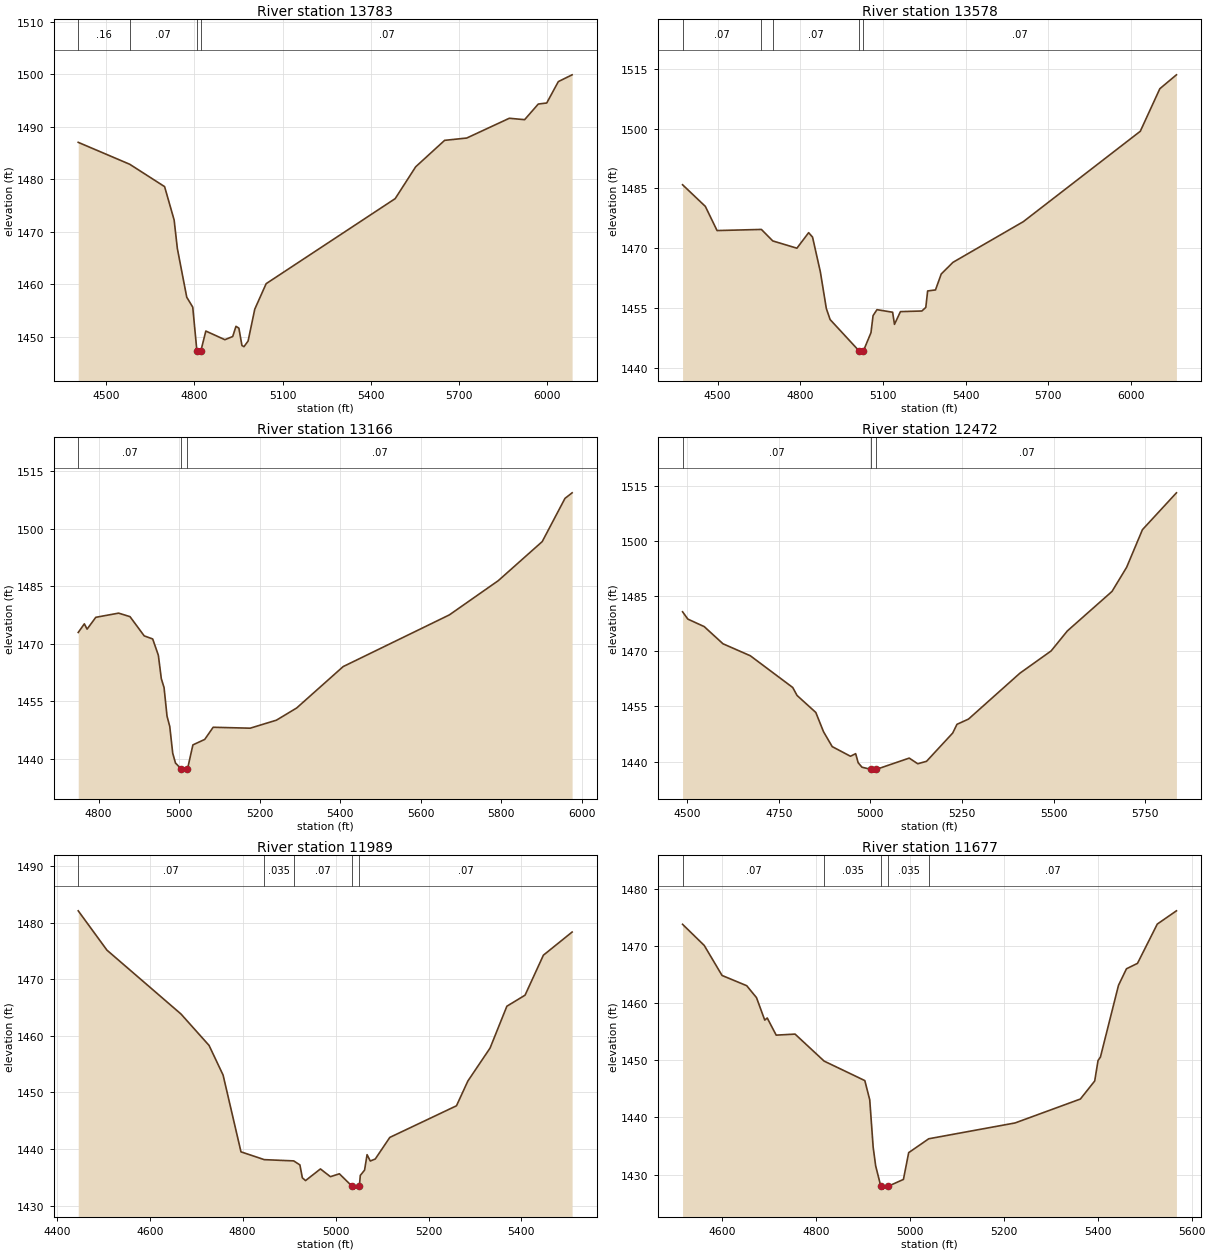
Type RM Length L Ch R = 1 ,13783   ,205,205,205
BEGIN DESCRIPTION:
Mapping XS 4287fcc9
END DESCRIPTION:
XS GIS Cut Line= 3
      1687921.24       7034675.6      1688100.93      7035251.14
      1689087.88      7035688.62
#Sta/Elev= 30
  4404.1 1487.03  4579.6 1482.85  4698.3 1478.59  4730.8 1472.23  4741.8 1466.78
  4773.8 1457.51  4794.2 1455.62  4808.2 1447.35  4808.7 1446.85  4822.2 1447.35
  4838.8 1451.06  4903.7 1449.41  4930.4 1450.02  4941.5 1451.96  4951.4 1451.61
  4961.8 1448.31  4968.7 1448.08  4982.8 1449.16  5005.5 1455.23  5044.3 1460.09
  5483.9  1476.3  5553.7 1482.37  5652.3 1487.41  5727.6 1487.85  5872.7 1491.62
  5924.8 1491.35  5971.3 1494.33  6000.1 1494.53  6039.7 1498.61  6086.6  1499.9
#Mann= 4 ,-1 , 0
  4404.1     .16       0  4579.6     .07       0  4808.2     .07       0
  4822.2     .07       0
Bank Sta=4808.2,4822.2
XS Rating Curve= 0 ,0
Exp/Cntr=0.3,0.1

Type RM Length L Ch R = 1 ,13578   ,412,412,412
BEGIN DESCRIPTION:
Mapping XS 9fd77e8c
END DESCRIPTION:
XS GIS Cut Line= 3
      1687488.93      7034967.27      1687955.09      7035391.76
      1688823.68      7036164.13
#Sta/Elev= 30
  4372.5 1485.91  4455.2 1480.49  4497.8 1474.43  4658.7 1474.71    4700 1471.83
  4787.6 1470.01  4830.2  1473.9  4844.4 1472.78  4872.8 1464.06  4894.4  1454.9
  4908.2 1452.12  5014.1 1444.21  5014.6 1443.71  5028.7 1444.21  5056.5 1448.84
  5064.1 1453.12  5078.3  1454.6  5135.1 1453.96  5141.8 1450.92  5163.4 1454.11
  5241.3 1454.27  5255.5 1455.17  5262.2 1459.29  5290.7 1459.55  5311.6 1463.55
  5354.2 1466.47  5609.3 1476.65  6034.1 1499.31  6105.1 1509.98  6165.3 1513.46
#Mann= 5 ,-1 , 0
  4372.5     .07       0  4658.7    .035       0    4700     .07       0
  5014.1     .07       0  5028.7     .07       0
Bank Sta=5014.1,5028.7
XS Rating Curve= 0 ,0
Exp/Cntr=0.3,0.1

Type RM Length L Ch R = 1 ,13166   ,694,694,694
BEGIN DESCRIPTION:
Mapping XS 9045b372
END DESCRIPTION:
XS GIS Cut Line= 3
      1687579.27      7035562.27      1687763.28      7035732.39
      1688554.53      7036303.27
#Sta/Elev= 30
  4749.4    1473  4764.6 1475.25  4771.4 1473.86    4793 1476.95  4849.7 1478.04
    4878 1477.12  4913.2 1472.11  4934.3  1471.3  4948.3 1467.07  4955.7 1460.94
  4962.5 1458.63  4969.9 1451.16  4976.7 1448.46    4984  1441.5  4990.9 1438.94
  5005.8 1437.33  5006.3 1436.83  5020.6 1437.33  5034.1 1443.67  5063.5  1445.1
  5084.4 1448.27  5176.4 1448.03  5241.5 1450.12  5291.8  1453.3  5407.1 1464.09
  5670.9 1477.58  5792.4 1486.51  5901.5  1496.7    5958 1507.97  5975.7 1509.42
#Mann= 3 ,-1 , 0
  4749.4     .07       0  5005.8     .07       0  5020.6     .07       0
Bank Sta=5005.8,5020.6
XS Rating Curve= 0 ,0
Exp/Cntr=0.3,0.1

Type RM Length L Ch R = 1 ,12472   ,483,483,483
BEGIN DESCRIPTION:
Mapping XS c98cc921
END DESCRIPTION:
XS GIS Cut Line= 3
       1687018.9      7036187.68       1687508.5      7036346.54
      1688281.01      7036659.96
#Sta/Elev= 30
  4487.1  1480.8  4501.6  1478.8  4546.1 1476.77  4597.5 1472.08  4672.2 1468.81
  4787.9 1460.17  4799.8 1457.99    4851 1453.36    4872 1448.11  4895.7 1444.06
  4945.6 1441.43  4959.7 1442.14  4966.6 1439.66  4977.1 1438.44    5001 1437.88
  5001.5 1437.38  5016.6 1437.88    5106 1440.93  5129.2 1439.39  5153.3 1440.06
  5224.7 1447.76  5236.3 1450.13  5267.8 1451.56  5408.1 1464.06  5493.4 1470.13
  5537.6 1475.57  5659.6 1486.34  5699.5 1492.91  5742.7 1503.17  5835.5 1513.21
#Mann= 3 ,-1 , 0
  4487.1     .07       0    5001     .07       0  5016.6     .07       0
Bank Sta=5001,5016.6
XS Rating Curve= 0 ,0
Exp/Cntr=0.3,0.1

Type RM Length L Ch R = 1 ,11989   ,312,312,312
BEGIN DESCRIPTION:
Mapping XS 5fa43f1e
END DESCRIPTION:
XS GIS Cut Line= 3
      1686847.17       7036583.4      1687365.36       7036778.7
      1687839.33       7036964.9
#Sta/Elev= 30
  4446.1 1482.11  4507.9 1475.16  4667.3 1463.87  4727.7 1458.32  4757.9 1453.08
  4796.4 1439.51  4846.6 1438.13  4909.9 1437.91  4923.2  1437.2  4928.5 1434.92
  4935.4 1434.43  4967.4 1436.49  4988.9 1435.12  5008.2 1435.63  5035.6 1433.42
  5036.1 1432.92  5051.2 1433.42  5053.2 1435.34  5062.4 1436.28  5067.8 1439.01
  5074.7 1437.89  5085.4 1438.24  5116.7 1442.06  5260.2 1447.65  5284.7 1452.02
  5332.5 1457.85  5368.7 1465.25  5407.8  1467.2  5447.3 1474.27  5509.1 1478.36
#Mann= 5 ,-1 , 0
  4446.1     .07       0  4846.6    .035       0  4909.9     .07       0
  5035.6     .07       0  5051.2     .07       0
Bank Sta=5035.6,5051.2
XS Rating Curve= 0 ,0
Exp/Cntr=0.3,0.1

Type RM Length L Ch R = 1 ,11677   ,465,465,465
BEGIN DESCRIPTION:
Mapping XS 8d10e930
END DESCRIPTION:
XS GIS Cut Line= 3
      1686724.74      7036859.43      1687188.28      7037006.57
      1687746.84      7037100.31
#Sta/Elev= 30
  4514.9 1473.82  4561.1 1470.12  4599.1 1464.86  4651.6 1463.07  4672.5 1460.98
  4690.1 1457.04  4695.4 1457.41  4714.5 1454.41  4754.7 1454.59  4816.7 1449.86
  4903.4 1446.45  4913.9 1443.08  4921.2 1434.78  4926.5 1431.52  4937.5 1427.94
    4938 1427.44  4953.1 1427.94  4985.7 1429.14  4996.9 1433.83  5039.7 1436.26
  5223.7 1439.03  5362.9 1443.22  5393.4 1446.38  5400.5 1449.96  5405.6 1450.57
  5444.1 1463.13  5461.1 1466.03  5484.6 1466.98  5526.8 1473.86  5567.6 1476.18
#Mann= 5 ,-1 , 0
  4514.9     .07       0  4816.7    .035       0  4937.5    .035       0
  4953.1    .035       0  5039.7     .07       0
Bank Sta=4937.5,4953.1
XS Rating Curve= 0 ,0
Exp/Cntr=0.3,0.1

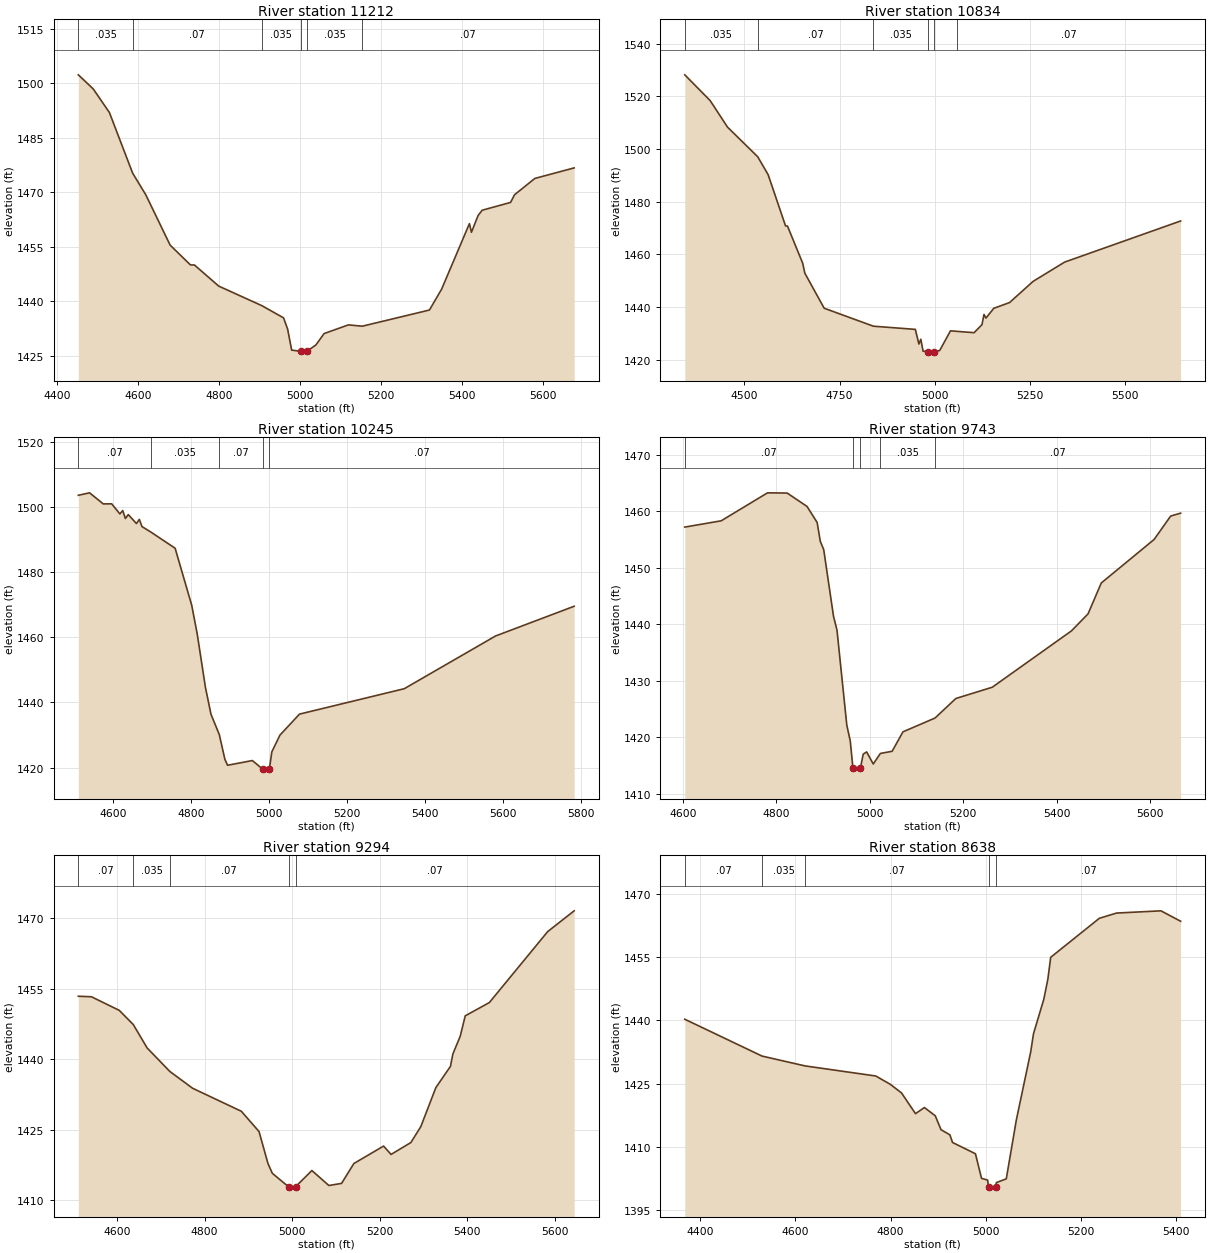
Type RM Length L Ch R = 1 ,11212   ,378,378,378
BEGIN DESCRIPTION:
Mapping XS c2dffcec
END DESCRIPTION:
XS GIS Cut Line= 3
      1686458.28      7037410.43      1687003.38      7037387.86
      1687681.94      7037348.05
#Sta/Elev= 30
  4452.9 1502.36  4489.7 1498.48  4529.7 1491.99  4587.1 1475.31  4619.8 1469.31
  4679.8  1455.5  4729.9 1450.06  4739.9 1450.03  4799.9 1444.22  4906.5 1438.84
  4960.1 1435.48  4970.1  1432.4  4980.1 1426.61  5002.3 1426.28  5002.8 1425.78
    5018 1426.28  5040.2 1428.05  5060.2 1431.16  5120.3 1433.55  5154.6 1433.19
  5320.6 1437.64  5350.7 1443.39  5419.4 1461.42  5424.4 1459.04  5440.9 1463.66
  5450.9  1465.1    5521 1467.25    5531 1469.37  5581.1 1473.85  5678.2 1476.75
#Mann= 6 ,-1 , 0
  4452.9    .035       0  4587.1     .07       0  4906.5    .035       0
  5002.3    .035       0    5018    .035       0  5154.6     .07       0
Bank Sta=5002.3,5018
XS Rating Curve= 0 ,0
Exp/Cntr=0.3,0.1

Type RM Length L Ch R = 1 ,10834   ,589,589,589
BEGIN DESCRIPTION:
Mapping XS efddcb0c
END DESCRIPTION:
XS GIS Cut Line= 3
      1686361.58      7037895.55      1687006.07      7037765.35
      1687629.76      7037602.93
#Sta/Elev= 30
  4343.5 1528.17  4410.1 1518.39  4455.7 1508.33  4535.1 1497.06  4562.4 1490.27
    4608 1470.87  4613.1  1470.8  4653.1 1456.68  4658.8 1452.89  4709.5 1439.61
  4838.7 1432.79  4948.9 1431.58  4958.2 1426.02  4963.3 1427.83  4969.3  1423.3
  4981.8 1423.07  4982.3 1422.57  4997.6 1423.07  5012.9 1423.57  5041.2 1431.04
  5057.1 1430.84  5103.2 1430.33  5123.9 1433.38  5129.2 1437.25  5134.4 1435.87
  5154.9 1439.58  5196.2 1441.75  5258.2  1449.8  5340.9 1457.11  5645.5 1472.71
#Mann= 6 ,-1 , 0
  4343.5    .035       0  4535.1     .07       0  4838.7    .035       0
  4981.8    .035       0  4997.6    .035       0  5057.1     .07       0
Bank Sta=4981.8,4997.6
XS Rating Curve= 0 ,0
Exp/Cntr=0.3,0.1

Type RM Length L Ch R = 1 ,10245   ,502,502,502
BEGIN DESCRIPTION:
Mapping XS a1f8a571
END DESCRIPTION:
XS GIS Cut Line= 3
      1686800.25      7038623.95      1687133.57      7038267.19
      1687654.19       7037682.8
#Sta/Elev= 30
  4511.1 1503.53  4539.9 1504.28  4575.1 1500.88  4596.6 1500.91  4617.6 1497.81
  4624.9 1498.85  4631.7  1496.4  4639.1 1497.61  4660.1 1494.86  4667.4 1496.14
  4674.2 1493.94  4698.2 1492.16  4759.2 1487.29  4801.7 1469.83  4815.9 1460.97
  4836.9 1444.63  4851.1 1436.39  4872.4 1430.17  4886.7 1422.59  4893.6 1420.75
  4957.2 1422.19  4984.8 1419.45  4985.3 1418.95  5000.6 1419.45    5007 1424.84
  5027.9 1429.99    5078 1436.43  5346.5 1444.22  5580.6 1460.39    5782  1469.5
#Mann= 5 ,-1 , 0
  4511.1     .07       0  4698.2    .035       0  4872.4     .07       0
  4984.8     .07       0  5000.6     .07       0
Bank Sta=4984.8,5000.6
XS Rating Curve= 0 ,0
Exp/Cntr=0.3,0.1

Type RM Length L Ch R = 1 ,9743    ,449,449,449
BEGIN DESCRIPTION:
Mapping XS c2f4d465
END DESCRIPTION:
XS GIS Cut Line= 3
      1687154.21       7038897.1       1687445.9      7038628.85
      1687923.74      7038166.63
#Sta/Elev= 30
  4603.9 1457.21  4681.8 1458.32    4781 1463.27    4823 1463.23  4865.5 1460.86
  4887.1 1458.03  4893.9 1454.69  4901.2 1453.23  4922.2 1441.41  4929.6    1439
  4950.6 1422.17    4958 1419.39  4963.8 1414.54  4964.3 1414.04  4979.7 1414.54
  4985.7 1417.04  4993.1 1417.44  5007.2  1415.3  5022.5 1417.17  5047.6 1417.55
  5070.8 1420.99  5139.4 1423.43    5184 1426.89  5261.9 1428.88  5431.4 1438.85
  5466.9 1441.86  5495.2 1447.32  5608.4 1455.03  5643.7 1459.16    5665 1459.68
#Mann= 5 ,-1 , 0
  4603.9     .07       0  4963.8     .07       0  4979.7     .07       0
  5022.5    .035       0  5139.4     .07       0
Bank Sta=4963.8,4979.7
XS Rating Curve= 0 ,0
Exp/Cntr=0.3,0.1

Type RM Length L Ch R = 1 ,9294    ,656,656,656
BEGIN DESCRIPTION:
Mapping XS fc723a19
END DESCRIPTION:
XS GIS Cut Line= 3
      1687316.98      7038956.98      1687796.16      7038884.06
      1688379.48      7038602.77
#Sta/Elev= 30
  4511.8 1453.44  4541.7 1453.33  4605.3 1450.43  4637.4  1447.4  4668.9 1442.43
  4720.7 1437.43  4772.8 1433.84  4884.1 1428.94  4924.5 1424.62  4944.8 1417.83
  4954.9 1415.72  4991.9 1412.86  4992.4 1412.36  5007.8 1412.86  5045.1 1416.32
    5084 1413.13  5112.9 1413.58  5141.1 1417.82  5208.9 1421.53    5226 1419.75
  5271.2 1422.28  5293.8 1425.65  5328.3 1433.99  5361.6  1438.5  5367.2 1441.16
  5383.8 1444.89  5395.4 1449.27  5450.4 1452.09  5583.6  1467.2  5644.1 1471.63
#Mann= 5 ,-1 , 0
  4511.8     .07       0  4637.4    .035       0  4720.7     .07       0
  4991.9     .07       0  5007.8     .07       0
Bank Sta=4991.9,5007.8
XS Rating Curve= 0 ,0
Exp/Cntr=0.3,0.1

Type RM Length L Ch R = 1 ,8638    ,399,399,399
BEGIN DESCRIPTION:
Mapping XS 1d7f0ed7
END DESCRIPTION:
XS GIS Cut Line= 3
      1687457.48      7039062.17      1688044.73      7039300.46
      1688384.59      7039525.73
#Sta/Elev= 30
  4367.9 1440.28  4530.2 1431.54  4620.6 1429.21    4769 1426.82    4799 1424.89
  4823.1 1422.81  4852.5 1417.89  4871.2 1419.34    4894 1417.39  4906.1 1414.09
  4924.8 1412.86  4930.2 1411.06  4978.4 1408.38  4991.2 1402.55    5004 1402.13
  5005.9 1400.49  5006.4 1399.99    5022 1400.49  5022.2 1401.53  5043.2 1402.43
  5064.3 1416.38  5094.4 1432.48  5100.4 1436.86    5122 1445.01  5130.5 1449.75
  5136.5 1454.97  5238.7 1464.22  5274.8 1465.46  5368.1 1465.99  5409.4 1463.52
#Mann= 5 ,-1 , 0
  4367.9     .07       0  4530.2    .035       0  4620.6     .07       0
  5005.9     .07       0    5022     .07       0
Bank Sta=5005.9,5022
XS Rating Curve= 0 ,0
Exp/Cntr=0.3,0.1