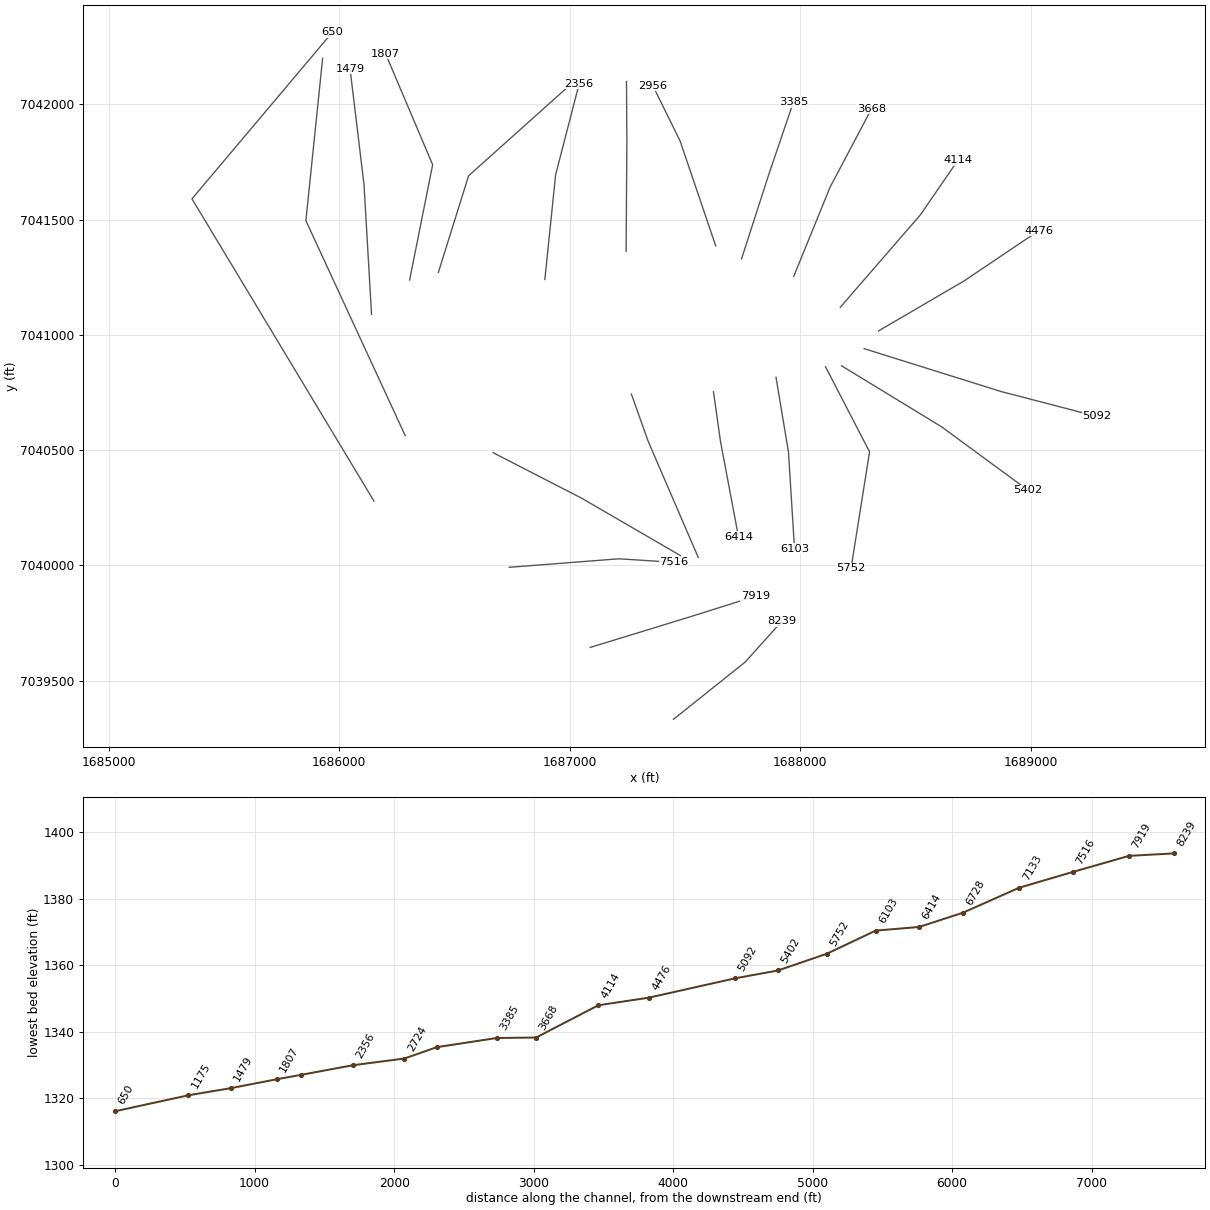
HEC-RAS study Chimney Creek 1190.prj: Chimney Creek 1190 Base Level Engineering

--- Chimney Creek 1190.g01 (geometry) --- (continued)

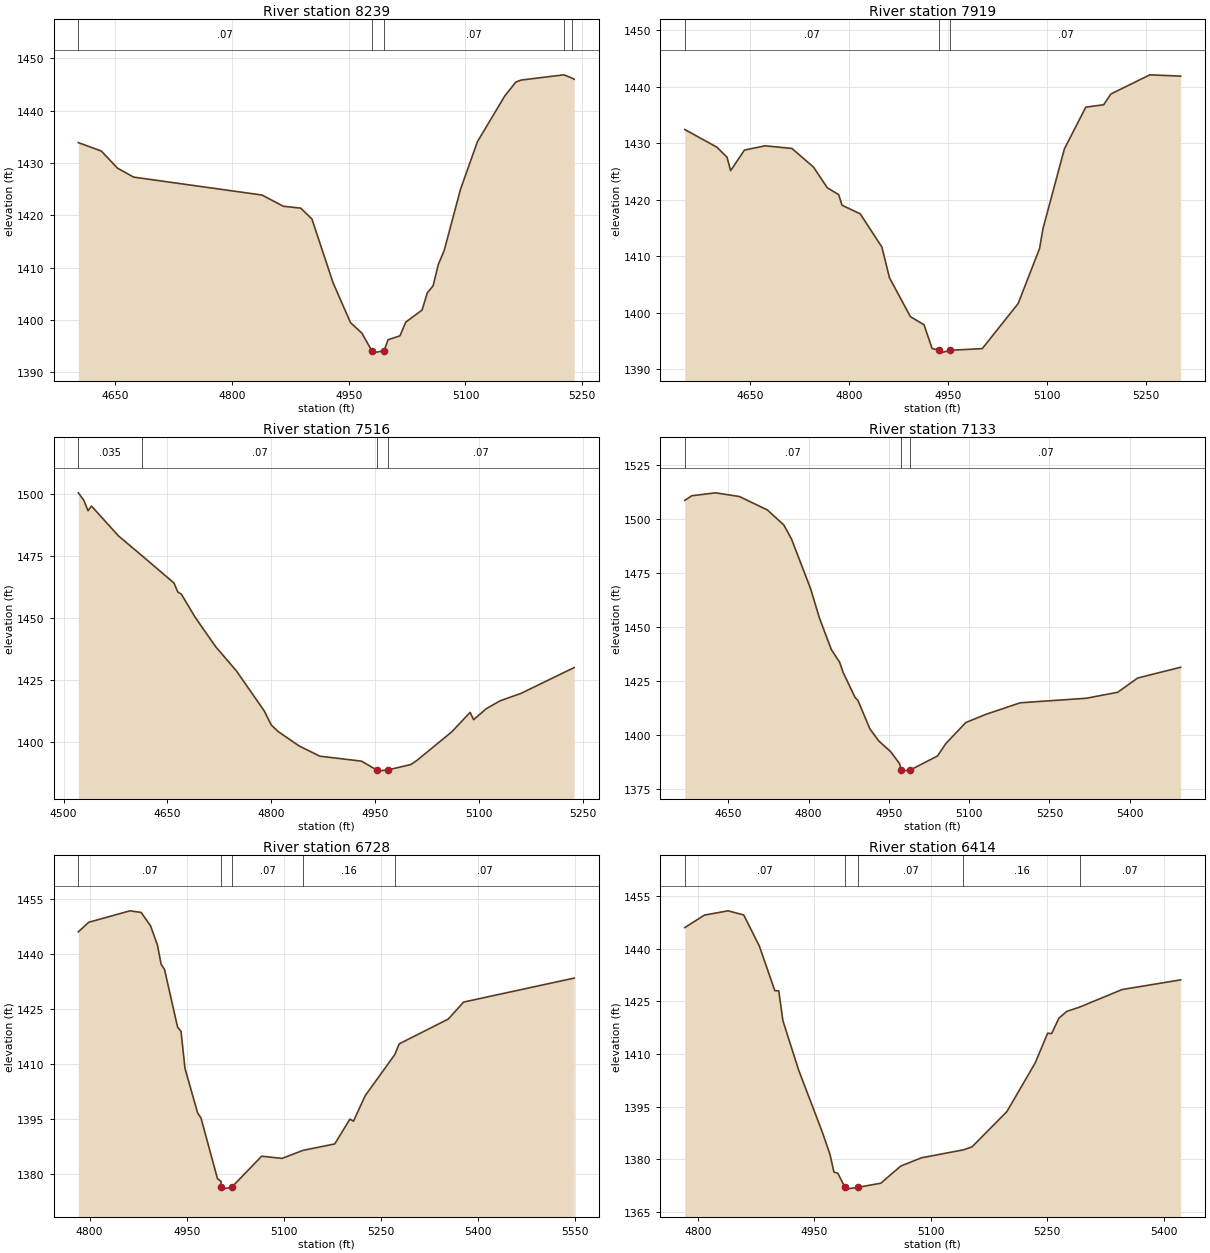
Type RM Length L Ch R = 1 ,8239    ,320,320,320
BEGIN DESCRIPTION:
Mapping XS d491d7e0
END DESCRIPTION:
XS GIS Cut Line= 3
      1687449.59      7039332.49      1687761.02      7039580.99
      1687920.26      7039758.64
#Sta/Elev= 30
  4602.6 1433.89  4632.1 1432.29  4652.9 1429.01  4673.7 1427.29  4838.7 1423.86
  4865.9 1421.72  4888.3 1421.36  4902.7 1419.28  4929.9 1407.07  4952.3 1399.45
  4966.8 1397.46  4979.5 1394.12    4980 1393.62  4995.6 1394.12  5000.4 1396.17
  5015.8 1396.93  5023.3 1399.56  5044.2 1401.86  5050.9 1405.13  5058.4  1406.5
  5065.1  1410.6  5072.6 1413.24  5093.6 1424.97  5115.3 1434.06  5150.4  1442.8
  5164.6 1445.47  5171.6 1445.86  5226.4 1446.86  5236.9 1446.24  5239.6 1446.01
#Mann= 5 ,-1 , 0
  4602.6     .07       0  4979.5     .07       0  4995.6     .07       0
  5226.4    .035       0  5236.9     .07       0
Bank Sta=4979.5,4995.6
XS Rating Curve= 0 ,0
Exp/Cntr=0.3,0.1

Type RM Length L Ch R = 1 ,7919    ,403,403,403
BEGIN DESCRIPTION:
Mapping XS d4c0ec22
END DESCRIPTION:
XS GIS Cut Line= 3
      1687088.68      7039644.34      1687519.27       7039776.3
      1687805.72      7039866.58
#Sta/Elev= 30
  4551.7 1432.43  4600.2 1429.31  4615.6 1427.54  4621.1 1425.16    4642 1428.79
  4673.4 1429.55  4713.9 1429.08  4746.6 1425.78  4767.5 1422.12  4784.6 1420.92
  4789.8 1419.04  4817.4 1417.51  4850.1 1411.64  4861.6 1406.21  4893.3 1399.33
  4913.9  1397.9  4926.1  1393.7  4937.2 1393.38  4937.7 1392.88  4953.4 1393.38
  5002.1 1393.68  5056.4 1401.65  5088.8 1411.37    5094 1414.89  5126.4 1428.99
  5158.8 1436.38  5185.9 1436.81  5196.8 1438.71  5255.8  1442.1  5302.4 1441.87
#Mann= 3 ,-1 , 0
  4551.7     .07       0  4937.2     .07       0  4953.4     .07       0
Bank Sta=4937.2,4953.4
XS Rating Curve= 0 ,0
Exp/Cntr=0.3,0.1

Type RM Length L Ch R = 1 ,7516    ,383,383,383
BEGIN DESCRIPTION:
Mapping XS 006fa7e5
END DESCRIPTION:
XS GIS Cut Line= 3
      1686737.07      7039991.84      1687212.35      7040028.73
      1687451.66      7040013.64
#Sta/Elev= 30
  4521.3 1500.61  4529.3 1497.58  4535.3 1493.39  4540.3 1495.27  4579.4 1483.16
    4614 1475.02  4659.6 1464.11  4665.1 1460.47  4670.1 1459.65  4689.7 1450.46
  4719.8 1438.36  4749.9 1428.53  4789.9 1412.42  4800.1 1406.71  4810.1 1404.05
  4840.2 1398.25  4870.3 1394.09  4930.5 1392.07  4952.4 1388.54  4952.9 1388.04
  4968.7 1388.54  5001.8  1390.7  5010.7  1392.4  5060.8  1403.9  5087.5 1411.81
  5092.5 1408.85  5110.9 1413.31  5130.9  1416.5    5161 1419.49  5237.8 1429.93
#Mann= 4 ,-1 , 0
  4521.3    .035       0    4614     .07       0  4952.4     .07       0
  4968.7     .07       0
Bank Sta=4952.4,4968.7
XS Rating Curve= 0 ,0
Exp/Cntr=0.3,0.1

Type RM Length L Ch R = 1 ,7133    ,405,405,405
BEGIN DESCRIPTION:
Mapping XS a674f0ec
END DESCRIPTION:
XS GIS Cut Line= 3
      1686667.69      7040488.78      1687051.76      7040291.32
      1687479.66      7040042.79
#Sta/Elev= 30
  4568.6 1508.45  4581.8 1510.63  4626.2 1511.96  4670.6 1510.25    4723 1504.04
  4753.7 1497.09    4768 1490.63  4803.6 1467.74  4820.2 1454.15  4842.4 1439.55
  4857.9  1433.7  4864.6  1428.9  4886.7 1417.45  4892.4  1415.9  4914.5 1402.89
  4931.1 1397.27  4953.3 1392.32  4969.8 1386.86  4973.5 1383.82    4974 1383.32
  4989.8 1383.82  5040.8  1390.3  5056.5 1396.07  5093.8 1405.77  5131.1 1409.55
  5195.6 1414.91    5319    1417  5377.7 1419.78    5415 1426.35  5495.3 1431.34
#Mann= 3 ,-1 , 0
  4568.6     .07       0  4973.5     .07       0  4989.8     .07       0
Bank Sta=4973.5,4989.8
XS Rating Curve= 0 ,0
Exp/Cntr=0.3,0.1

Type RM Length L Ch R = 1 ,6728    ,314,314,314
BEGIN DESCRIPTION:
Mapping XS 99eb09c2
END DESCRIPTION:
XS GIS Cut Line= 3
      1687267.05      7040743.13      1687339.96      7040538.28
      1687556.98       7040034.8
#Sta/Elev= 30
  4782.7 1445.97  4798.8 1448.58  4862.4  1451.7  4879.7 1451.27  4894.3 1447.59
  4904.9 1442.36  4910.5 1437.16  4915.8 1435.71    4936 1419.97  4941.3 1418.79
  4947.4 1408.73  4966.9 1396.59  4972.2 1395.16  4997.6 1378.62  5003.1 1377.91
  5003.2 1376.28  5003.7 1375.78  5019.5 1376.28  5065.8 1384.77  5097.2 1384.16
  5129.7 1386.36  5178.6  1388.1  5202.1 1394.88  5207.6 1394.31  5225.6 1401.24
  5271.7 1412.56  5278.1  1415.4  5353.9 1422.16  5377.7 1426.81  5548.4 1433.35
#Mann= 5 ,-1 , 0
  4782.7     .07       0  5003.2     .07       0  5019.5     .07       0
  5129.7     .16       0  5271.7     .07       0
Bank Sta=5003.2,5019.5
XS Rating Curve= 0 ,0
Exp/Cntr=0.3,0.1

Type RM Length L Ch R = 1 ,6414    ,311,311,311
BEGIN DESCRIPTION:
Mapping XS e19364be
END DESCRIPTION:
XS GIS Cut Line= 3
      1687623.09      7040753.14      1687653.47      7040538.34
      1687731.59      7040123.88
#Sta/Elev= 30
  4783.1 1445.99  4808.5 1449.54  4838.8 1450.75    4859 1449.58  4879.2 1440.69
  4899.1    1428  4904.1 1427.97  4909.5 1419.47  4929.7 1405.43    4960 1387.88
  4970.1 1381.42  4975.2 1376.35  4980.2 1376.01  4989.5 1371.99    4990 1371.49
  5005.8 1371.99  5035.6 1373.18  5061.4 1378.08  5088.1 1380.42  5141.8 1382.67
    5153 1383.51    5198 1393.57  5234.4 1407.41  5250.5 1415.89  5255.6 1415.79
    5265 1420.18  5275.1 1422.11  5291.8 1423.34  5346.4 1428.33  5421.8 1431.09
#Mann= 5 ,-1 , 0
  4783.1     .07       0  4989.5     .07       0  5005.8     .07       0
  5141.8     .16       0  5291.8     .07       0
Bank Sta=4989.5,5005.8
XS Rating Curve= 0 ,0
Exp/Cntr=0.3,0.1

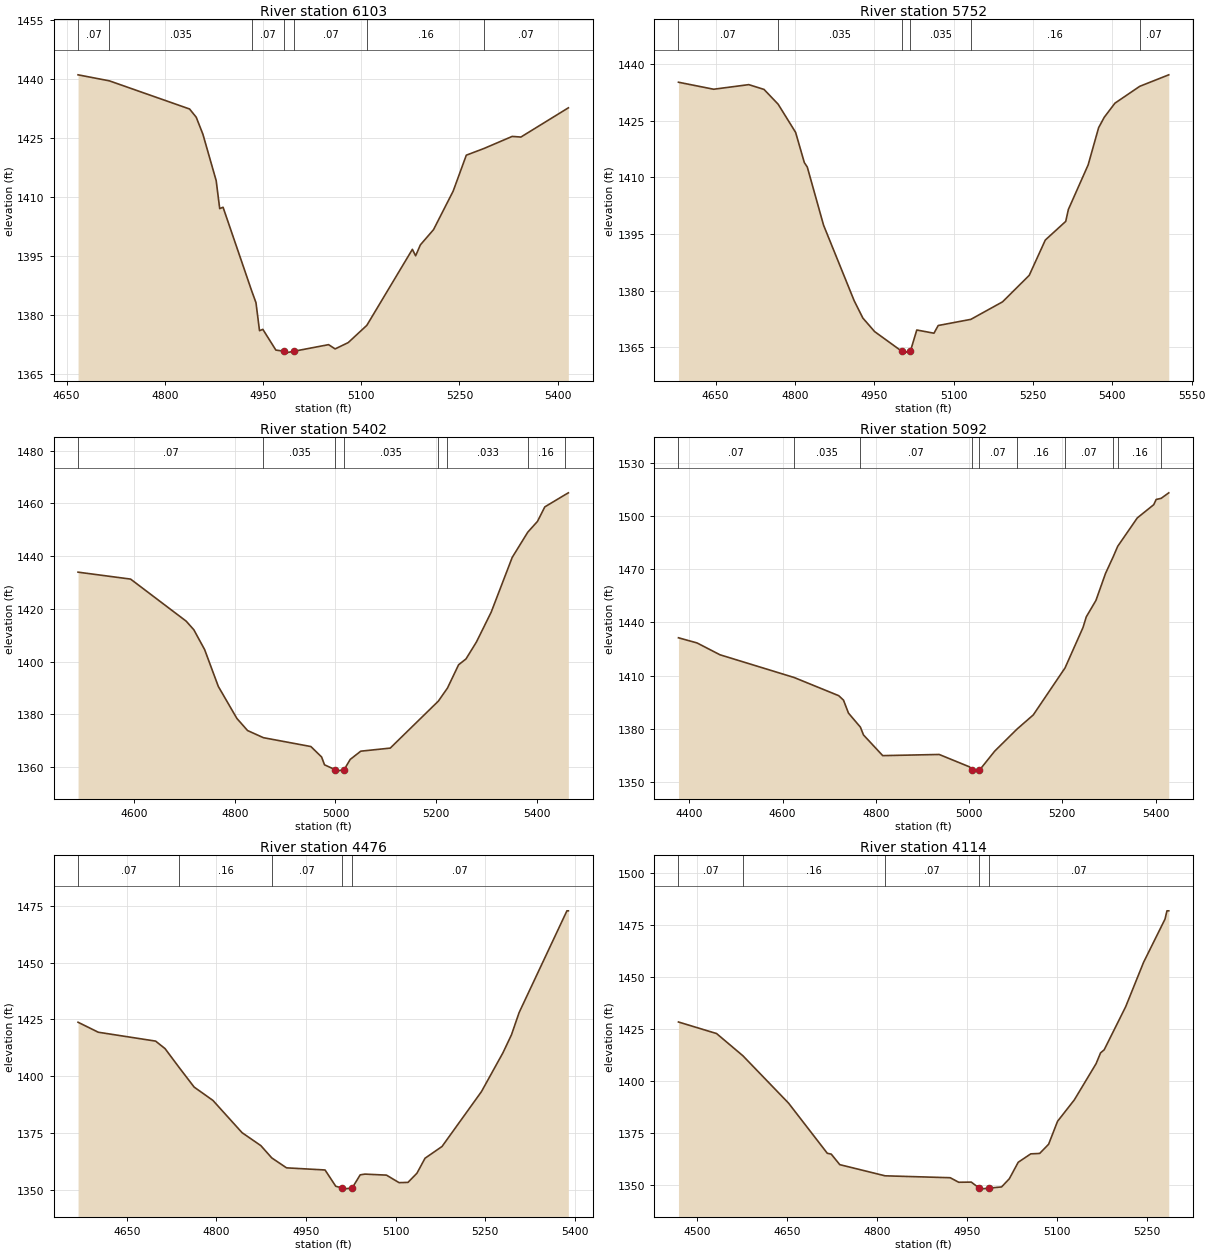
Type RM Length L Ch R = 1 ,6103    ,351,351,351
BEGIN DESCRIPTION:
Mapping XS 3b6ae654
END DESCRIPTION:
XS GIS Cut Line= 3
      1687894.36      7040816.08      1687948.61       7040490.6
      1687974.61      7040072.38
#Sta/Elev= 30
  4667.4 1440.98  4715.3 1439.45  4837.8 1432.31  4847.9 1430.23  4858.1 1425.93
  4878.4 1414.15  4883.8 1407.05  4888.9  1407.4  4932.4 1386.31  4939.2 1383.19
  4944.6 1376.09  4949.7 1376.43  4969.6 1371.17  4981.7  1370.9  4982.2  1370.4
    4998  1370.9  5050.1 1372.55  5060.1 1371.47  5080.1 1373.07  5108.5 1377.44
  5178.1 1396.72  5183.1 1395.08  5190.3 1397.85  5210.4 1401.71  5240.4 1411.48
  5260.5  1420.6  5287.8 1422.32  5330.6 1425.36  5343.9  1425.2  5416.4 1432.61
#Mann= 7 ,-1 , 0
  4667.4     .07       0  4715.3    .035       0  4932.4     .07       0
  4981.7     .07       0    4998     .07       0  5108.5     .16       0
  5287.8     .07       0
Bank Sta=4981.7,4998
XS Rating Curve= 0 ,0
Exp/Cntr=0.3,0.1

Type RM Length L Ch R = 1 ,5752    ,350,350,350
BEGIN DESCRIPTION:
Mapping XS 62cf1b50
END DESCRIPTION:
XS GIS Cut Line= 3
      1688109.21      7040861.67      1688300.17      7040492.77
      1688219.94      7039987.49
#Sta/Elev= 30
  4579.7 1435.24  4646.2 1433.38  4712.6  1434.6  4741.5 1433.33  4768.2 1429.41
  4801.2 1421.95  4817.7 1413.94  4823.3 1412.75  4854.1 1397.33  4911.9 1377.33
  4928.4 1372.72  4950.5 1369.15  5001.9 1363.93  5002.4 1363.43  5018.2 1363.93
  5030.3 1369.56  5062.8 1368.71  5070.8 1370.75  5132.5 1372.38  5192.4 1377.02
  5242.9 1384.05  5273.3 1393.41  5311.9 1398.35  5316.9 1401.51  5354.3 1413.33
  5374.1 1423.19  5384.7 1425.94  5404.9 1429.68  5451.9 1434.16  5506.7  1437.2
#Mann= 6 ,-1 , 0
  4579.7     .07       0  4768.2    .035       0  5001.9    .035       0
  5018.2    .035       0  5132.5     .16       0  5451.9     .07       0
Bank Sta=5001.9,5018.2
XS Rating Curve= 0 ,0
Exp/Cntr=0.3,0.1

Type RM Length L Ch R = 1 ,5402    ,310,310,310
BEGIN DESCRIPTION:
Mapping XS 9d946cec
END DESCRIPTION:
XS GIS Cut Line= 3
      1688178.63      7040866.04      1688612.67      7040601.27
      1688988.14      7040325.64
#Sta/Elev= 30
  4488.6 1433.91    4593 1431.28  4703.4 1415.32  4718.6 1412.06  4740.1 1404.52
  4767.3 1390.54  4804.1 1378.42  4825.4  1373.8  4856.9 1371.09  4951.2 1367.73
  4972.5 1363.77  4978.3 1360.79  5000.1  1358.9  5000.6  1358.4  5017.1  1358.9
  5029.4 1362.85  5050.3 1365.97  5108.9 1367.14  5204.5 1384.98  5222.6 1389.93
  5244.7 1398.76  5259.4 1400.98  5280.2 1407.43  5309.5 1418.75  5351.2  1439.5
  5382.1 1449.07  5401.4 1453.17    5416 1458.68  5455.4  1463.2  5462.8 1464.02
#Mann= 8 ,-1 , 0
  4488.6     .07       0  4856.9    .035       0  5000.1    .035       0
  5017.1    .035       0  5204.5     .16       0  5222.6    .033       0
  5382.1     .16       0  5455.4     .07       0
Bank Sta=5000.1,5017.1
XS Rating Curve= 0 ,0
Exp/Cntr=0.3,0.1

Type RM Length L Ch R = 1 ,5092    ,616,616,616
BEGIN DESCRIPTION:
Mapping XS 568e4ef2
END DESCRIPTION:
XS GIS Cut Line= 3
      1688277.03      7040940.26      1688869.47      7040754.72
      1689286.16      7040646.21
#Sta/Elev= 30
  4376.8  1431.3  4416.6 1428.39  4465.9  1421.7  4624.8 1408.88  4720.5 1398.61
  4730.7  1396.1  4741.4 1388.77    4767 1380.84  4773.6 1376.44  4814.8 1364.77
  4935.9 1365.42  5001.3 1358.39  5005.2 1356.52  5005.7 1356.02  5022.2 1356.52
    5055 1367.32  5102.6  1379.7  5137.7 1387.76  5205.8  1414.3  5244.3 1437.09
  5251.3 1443.11    5272 1452.37  5292.7  1467.7  5308.9 1476.93  5318.7 1482.93
  5360.7 1498.96    5396 1506.44  5401.2 1509.38    5412 1510.03  5428.2 1513.13
#Mann= 10 ,-1 , 0
  4376.8     .07       0  4624.8    .035       0    4767     .07       0
  5005.2     .07       0  5022.2     .07       0  5102.6     .16       0
  5205.8     .07       0  5308.9    .033       0  5318.7     .16       0
    5412     .07       0
Bank Sta=5005.2,5022.2
XS Rating Curve= 0 ,0
Exp/Cntr=0.3,0.1

Type RM Length L Ch R = 1 ,4476    ,362,362,362
BEGIN DESCRIPTION:
Mapping XS 54cab434
END DESCRIPTION:
XS GIS Cut Line= 3
      1688338.64      7041017.08      1688711.05      7041234.54
        1689034.      7041452.01
#Sta/Elev= 30
  4568.4 1423.77  4602.3 1419.37  4698.2 1415.46    4714 1412.15  4737.4  1403.9
  4762.7 1395.19  4794.1 1389.33  4842.9  1375.1  4874.3  1369.4  4892.6 1363.98
  4917.3  1359.6  4981.8 1358.66  4999.7 1351.49  5010.1 1350.72  5010.6 1350.22
  5027.2 1350.72  5040.6 1356.51  5048.6 1356.84  5084.6 1356.39  5105.6 1353.08
  5120.6 1353.19  5135.6 1357.24  5149.1 1363.83  5177.6 1369.03  5243.5 1393.18
  5279.5  1410.3  5293.8 1418.26  5306.6 1428.05  5386.6 1472.88    5389 1472.88
#Mann= 5 ,-1 , 0
  4568.4     .07       0  4737.4     .16       0  4892.6     .07       0
  5010.1     .07       0  5027.2     .07       0
Bank Sta=5010.1,5027.2
XS Rating Curve= 0 ,0
Exp/Cntr=0.3,0.1

Type RM Length L Ch R = 1 ,4114    ,446,446,446
BEGIN DESCRIPTION:
Mapping XS 0787ad42
END DESCRIPTION:
XS GIS Cut Line= 3
       1688173.3      7041119.96      1688520.95        7041521.
      1688683.69      7041757.95
#Sta/Elev= 30
  4468.5 1428.28  4532.1 1422.73    4576 1412.06  4652.2 1389.29  4716.9 1365.17
  4723.5 1364.76  4737.7 1359.71  4813.3 1354.34    4922 1353.42  4936.2 1351.24
  4957.1 1351.32  4970.4 1348.44  4970.9 1347.94  4987.5 1348.44  5007.7    1349
  5020.6 1352.91  5035.5 1360.86  5056.4 1364.89  5071.3  1365.1  5086.2 1369.51
  5101.1 1380.53  5129.1 1390.84  5165.4 1408.23  5172.9 1413.44  5178.9 1414.91
  5214.8 1435.62  5244.6 1456.92  5280.4 1477.71  5283.7 1481.72  5286.7 1481.72
#Mann= 5 ,-1 , 0
  4468.5     .07       0    4576     .16       0  4813.3     .07       0
  4970.4     .07       0  4987.5     .07       0
Bank Sta=4970.4,4987.5
XS Rating Curve= 0 ,0
Exp/Cntr=0.3,0.1

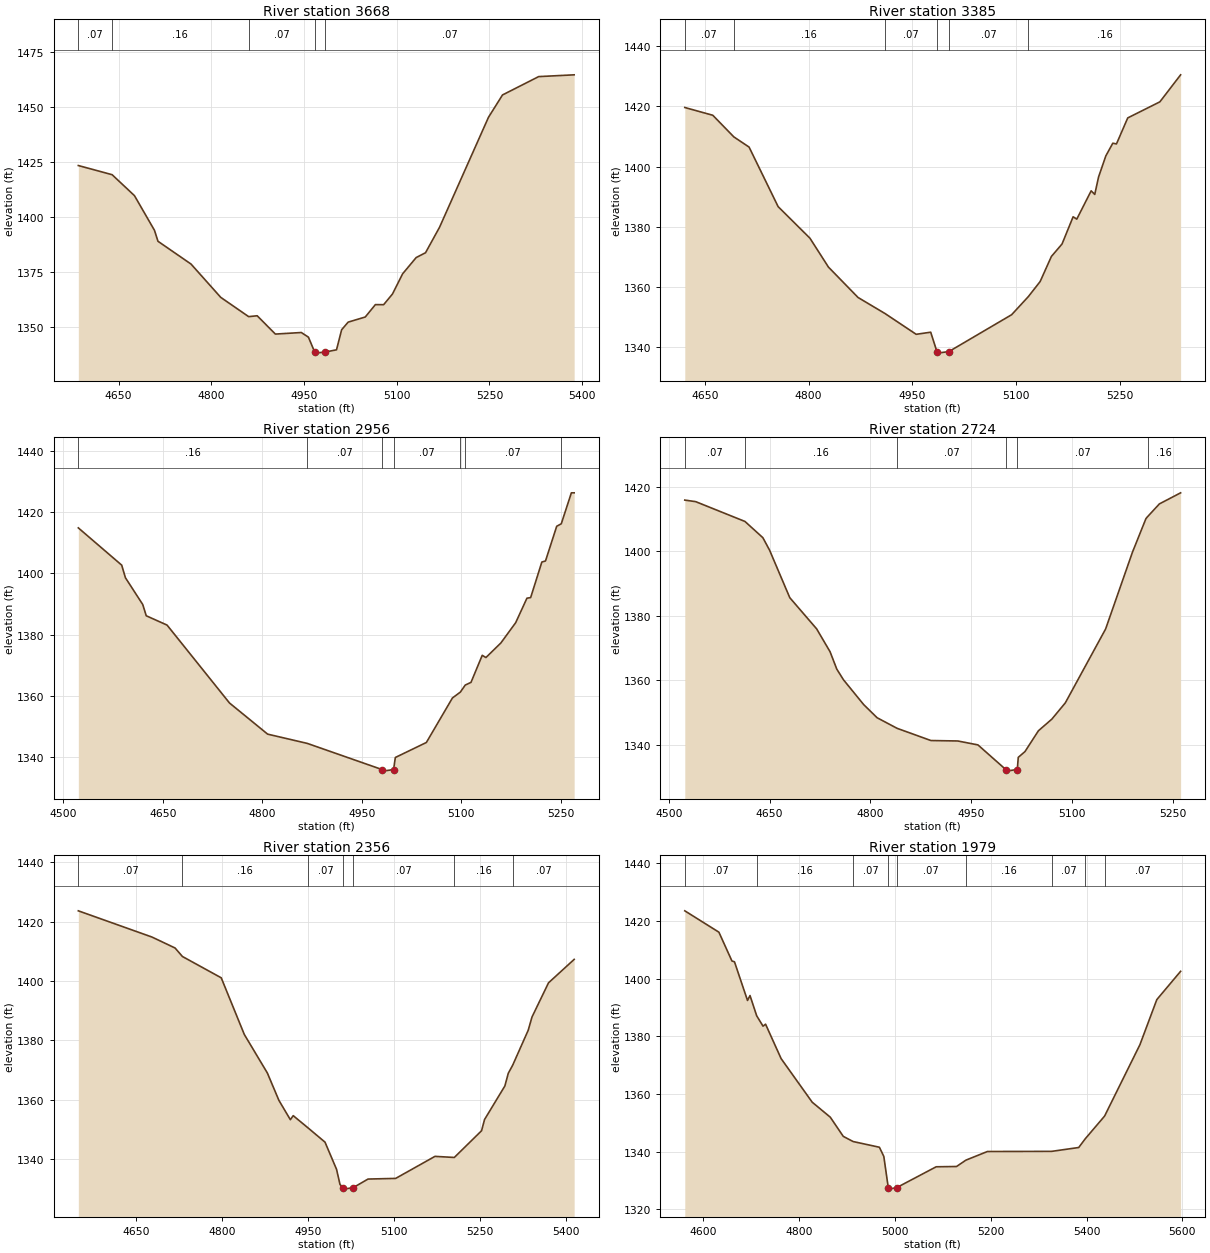
Type RM Length L Ch R = 1 ,3668    ,283,283,283
BEGIN DESCRIPTION:
Mapping XS 365922f8
END DESCRIPTION:
XS GIS Cut Line= 3
      1687971.35      7041253.93      1688128.91      7041640.68
      1688308.58      7041980.49
#Sta/Elev= 30
    4585 1423.52  4639.6 1419.36  4675.8 1409.83  4708.2 1394.05  4713.8 1389.09
  4767.3 1378.72  4815.4 1363.57  4860.5 1354.82  4874.3 1355.22  4903.7 1346.89
  4945.7  1347.6  4957.2 1345.48  4967.3 1338.73  4967.8 1338.23  4984.4 1338.73
  5002.6 1339.73  5010.9 1348.85  5021.4 1352.32  5049.1 1354.65  5065.5 1360.29
  5078.8 1360.25  5093.1 1365.09  5109.5 1374.27  5131.5 1381.69  5146.6 1383.87
  5169.3 1395.47  5248.4 1445.44  5271.1 1455.61  5329.6 1463.95    5387 1464.76
#Mann= 5 ,-1 , 0
    4585     .07       0  4639.6     .16       0  4860.5     .07       0
  4967.3     .07       0  4984.4     .07       0
Bank Sta=4967.3,4984.4
XS Rating Curve= 0 ,0
Exp/Cntr=0.3,0.1

Type RM Length L Ch R = 1 ,3385    ,429,429,429
BEGIN DESCRIPTION:
Mapping XS 4b2b299d
END DESCRIPTION:
XS GIS Cut Line= 3
       1687744.8       7041329.5      1687861.98      7041692.76
      1687970.03       7042010.4
#Sta/Elev= 30
  4620.9 1419.66  4661.4 1417.08  4691.8 1409.91  4713.9 1406.51  4755.9 1386.74
  4801.9 1376.26  4828.7 1366.66  4871.5 1356.57  4910.3 1351.27  4955.6 1344.34
  4976.6 1345.04  4985.6 1338.59  4986.1 1338.09  5002.8 1338.59  5093.7 1350.85
  5117.9 1356.88  5134.9 1361.86  5151.2  1370.2  5166.6 1374.34  5182.6 1383.37
  5187.9 1382.59  5208.7 1391.99  5213.9  1390.8  5219.4 1396.58  5229.9 1403.58
    5240  1407.8  5245.3 1407.56  5261.6  1416.2  5308.1 1421.54  5338.1 1430.51
#Mann= 6 ,-1 , 0
  4620.9     .07       0  4691.8     .16       0  4910.3     .07       0
  4985.6     .07       0  5002.8     .07       0  5117.9     .16       0
Bank Sta=4985.6,5002.8
XS Rating Curve= 0 ,0
Exp/Cntr=0.3,0.1

Type RM Length L Ch R = 1 ,2956    ,232,232,232
BEGIN DESCRIPTION:
Mapping XS 1d18eb67
END DESCRIPTION:
XS GIS Cut Line= 3
      1687632.93       7041386.1      1687478.41      7041840.98
      1687360.36      7042080.56
#Sta/Elev= 30
  4522.5  1414.9  4587.9 1402.71  4593.5 1398.59  4619.6 1389.84  4624.9 1386.15
  4656.3  1383.1  4750.4 1357.62  4807.9 1347.43  4867.7  1344.4  4980.6 1335.83
  4981.1 1335.33  4997.8 1335.83  5000.4 1339.79  5047.2  1344.7  5086.5 1359.26
  5098.4 1361.18  5105.8 1363.48  5114.5 1364.37  5131.4 1373.21    5137 1372.49
  5159.5 1377.25  5181.9 1383.91  5198.8  1391.9  5204.4  1392.1  5221.3 1403.73
  5226.8 1404.08  5243.7 1415.43  5250.6 1416.25  5265.8 1426.37    5270 1426.37
#Mann= 7 ,-1 , 0
  4522.5     .16       0  4867.7     .07       0  4980.6     .07       0
  4997.8     .07       0  5098.4     .16       0  5105.8     .07       0
  5250.6     .16       0
Bank Sta=4980.6,4997.8
XS Rating Curve= 0 ,0
Exp/Cntr=0.3,0.1

Type RM Length L Ch R = 1 ,2724    ,368,368,368
BEGIN DESCRIPTION:
Mapping XS dd853f1a
END DESCRIPTION:
XS GIS Cut Line= 3
      1687244.04      7041361.85      1687247.51      7041839.25
      1687245.77      7042099.63
#Sta/Elev= 30
  4523.8 1415.81    4540 1415.33  4613.3  1409.2    4640 1404.17    4650 1400.29
    4680 1385.61    4720 1375.95    4740 1368.86    4750 1363.48    4760 1360.17
    4790 1352.51    4810 1348.44  4839.7 1345.17    4890 1341.39    4930 1341.25
    4960 1340.04  5001.4 1332.42  5001.9 1331.92  5018.6 1332.42    5020 1336.18
    5030 1337.97    5050 1344.41    5070 1348.02    5090 1353.04    5150 1375.92
    5190 1399.72    5210 1410.08  5212.7 1410.74    5230 1414.63  5261.6 1418.06
#Mann= 6 ,-1 , 0
  4523.8     .07       0  4613.3     .16       0  4839.7     .07       0
  5001.4     .07       0  5018.6     .07       0  5212.7     .16       0
Bank Sta=5001.4,5018.6
XS Rating Curve= 0 ,0
Exp/Cntr=0.3,0.1

Type RM Length L Ch R = 1 ,2356    ,377,377,377
BEGIN DESCRIPTION:
Mapping XS e34439f9
END DESCRIPTION:
XS GIS Cut Line= 3
       1686891.6      7041240.26      1686938.48      7041695.15
      1687040.44      7042089.17
#Sta/Elev= 30
  4549.7  1423.6  4678.1 1414.77  4718.3 1411.09  4731.2 1408.22  4798.8 1401.05
    4839 1381.99  4879.2 1369.01  4899.3 1359.81  4919.3 1353.28  4924.3 1354.64
  4949.2 1350.67  4979.7 1345.73  4999.8 1336.58  5005.9 1331.44  5011.6 1330.41
  5012.1 1329.91  5028.9 1330.41  5054.7  1333.3  5102.9 1333.52  5171.4 1340.94
  5205.1 1340.57  5252.6 1349.57  5257.8 1353.34  5293.2 1364.63  5299.2 1368.92
  5306.9 1371.65  5333.9 1383.39  5340.5 1387.85  5369.3 1399.36    5414 1407.25
#Mann= 7 ,-1 , 0
  4549.7     .07       0  4731.2     .16       0  4949.2     .07       0
  5011.6     .07       0  5028.9     .07       0  5205.1     .16       0
  5306.9     .07       0
Bank Sta=5011.6,5028.9
XS Rating Curve= 0 ,0
Exp/Cntr=0.3,0.1

Type RM Length L Ch R = 1 ,1979    ,172,172,172
BEGIN DESCRIPTION:
Chimney Creek 1190 4.0
END DESCRIPTION:
XS GIS Cut Line= 3
      1686429.81      7041271.57      1686560.88      7041690.13
      1687005.02      7042088.02
#Sta/Elev= 30
  4561.4 1423.53  4632.6 1416.12  4659.8 1406.12  4665.1 1405.85  4692.3 1392.43
  4697.5 1394.14  4711.5  1387.1  4724.7 1383.52    4730  1384.2  4762.4 1372.27
  4827.3 1357.14    4865 1351.95  4892.2 1345.28  4912.7 1343.49  4967.6 1341.51
  4976.8 1338.32  4986.1 1327.48  4986.6 1326.98  5003.4 1327.48  5086.1 1334.73
  5128.6 1334.83  5148.1 1337.03    5193 1340.03  5327.1 1340.08  5383.6 1341.42
  5397.3 1344.46  5437.6 1352.32  5511.4  1377.1  5546.6 1392.73  5596.3 1402.55
#Mann= 9 ,-1 , 0
  4561.4     .07       0  4711.5     .16       0  4912.7     .07       0
  4986.1     .07       0  5003.4     .07       0  5148.1     .16       0
  5327.1     .07       0  5397.3     .16       0  5437.6     .07       0
Bank Sta=4986.1,5003.4
XS Rating Curve= 0 ,0
Exp/Cntr=0.3,0.1

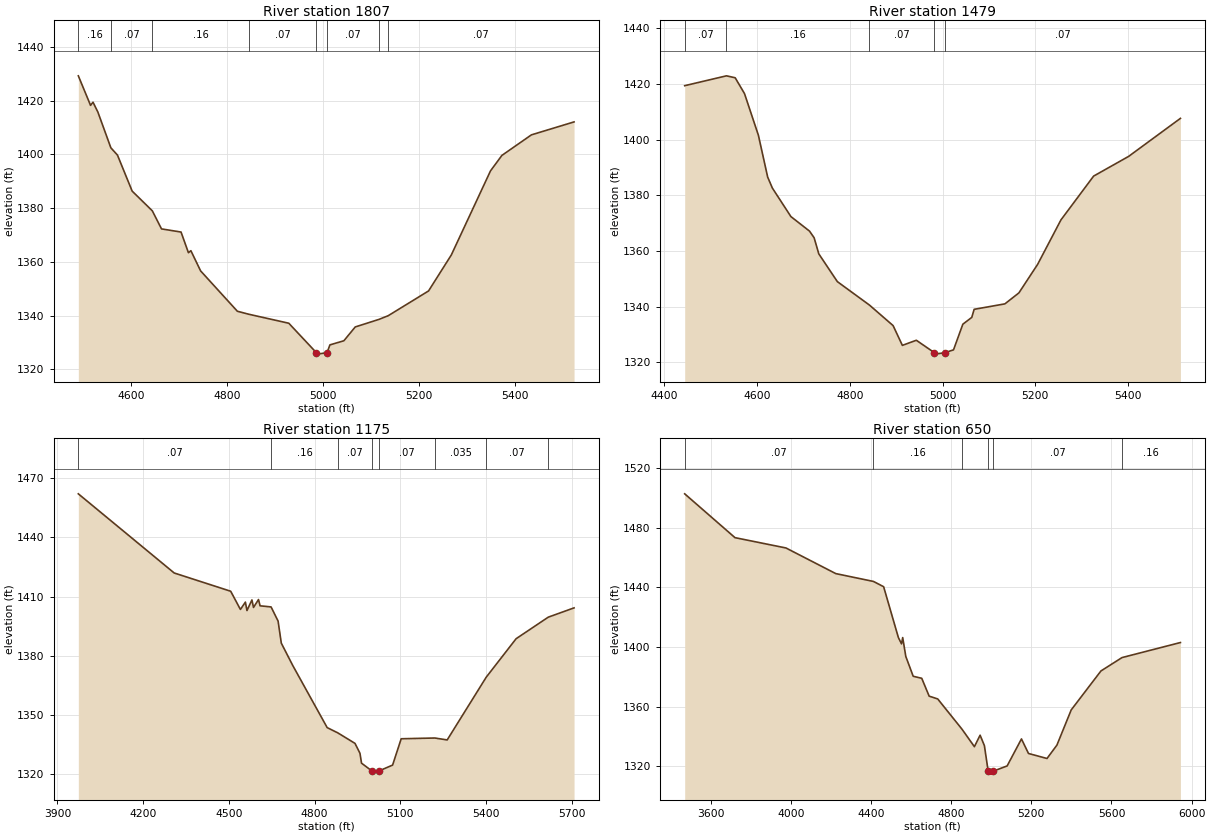
Type RM Length L Ch R = 1 ,1807    ,328,328,328
BEGIN DESCRIPTION:
Chimney Creek 1190 3.0
END DESCRIPTION:
XS GIS Cut Line= 3
        1686305.        7041238.      1686404.95      7041738.11
      1686200.57      7042219.85
#Sta/Elev= 30
    4490 1429.19  4515.5  1418.2  4520.6 1419.39  4530.8 1415.69  4557.8 1402.42
  4571.6  1399.7  4602.2 1386.31  4644.2 1378.98  4663.4 1372.25  4704.1 1371.08
  4719.5 1363.39  4724.6 1364.15  4744.9 1356.63  4821.5 1341.62  4845.2 1340.51
  4928.7 1337.16  4986.4 1326.17  4986.9 1325.67  5008.4 1326.17  5014.4 1329.11
  5043.5 1330.64  5067.2 1335.78  5117.1 1338.62    5136 1339.97    5220 1349.17
  5267.4 1362.54  5349.2 1393.85  5372.9 1399.59  5434.4 1407.23  5523.3 1412.05
#Mann= 8 ,-1 , 0
    4490     .16       0  4557.8     .07       0  4644.2     .16       0
  4845.2     .07       0  4986.4     .07       0  5008.4     .07       0
  5117.1    .035       0    5136     .07       0
Bank Sta=4986.4,5008.4
XS Rating Curve= 0 ,0
Exp/Cntr=0.3,0.1

Type RM Length L Ch R = 1 ,1479    ,304,304,304
BEGIN DESCRIPTION:
Mapping XS 0240d63d
END DESCRIPTION:
XS GIS Cut Line= 3
      1686139.79      7041089.26      1686107.24       7041651.3
      1686046.59      7042153.87
#Sta/Elev= 30
  4443.9 1419.36    4534  1422.9  4552.8  1422.2  4572.9 1416.52  4602.9 1401.55
  4622.9 1386.54    4633 1382.61    4673 1372.37  4713.1 1367.16  4723.1 1364.76
  4733.1    1359  4773.2 1349.02  4842.3 1340.62  4893.4 1333.24  4913.4 1326.14
  4943.5 1327.98  4982.6  1323.5  4983.1    1323  5004.6  1323.5  5023.7 1324.53
  5043.8 1333.74  5063.1 1336.19  5068.2 1339.08  5134.5 1341.04  5164.7 1344.98
    5205 1355.19  5255.4 1371.18  5325.9 1386.91  5401.3 1393.97  5513.1 1407.63
#Mann= 5 ,-1 , 0
  4443.9     .07       0    4534     .16       0  4842.3     .07       0
  4982.6     .07       0  5004.6     .07       0
Bank Sta=4982.6,5004.6
XS Rating Curve= 0 ,0
Exp/Cntr=0.3,0.1

Type RM Length L Ch R = 1 ,1175    ,525,525,525
BEGIN DESCRIPTION:
Mapping XS d61daba1
END DESCRIPTION:
XS GIS Cut Line= 3
      1686285.71      7040563.43      1685855.01      7041495.53
      1685927.64      7042199.69
#Sta/Elev= 30
  3973.2 1462.15  4308.7 1421.96  4506.4 1412.69  4540.4 1403.44  4557.8 1407.18
  4563.3 1402.89  4580.7 1408.28  4586.2 1404.47  4603.7 1408.48  4609.2 1405.29
  4647.7 1404.73  4672.2 1397.54  4683.5 1386.34  4723.8 1374.93    4844 1343.46
  4880.7 1340.83  4941.3 1335.46  4958.7 1330.44  4964.2 1325.41  5001.5 1321.36
    5002 1320.86  5023.6 1321.36  5072.9 1324.43    5103  1337.8  5220.8 1338.18
  5263.9  1337.2  5400.7 1369.09  5505.1 1388.59  5617.6 1399.53  5707.9 1404.25
#Mann= 8 ,-1 , 0
  3973.2     .07       0  4647.7     .16       0  4880.7     .07       0
  5001.5     .07       0  5023.6     .07       0  5220.8    .035       0
  5400.7     .07       0  5617.6     .16       0
Bank Sta=5001.5,5023.6
XS Rating Curve= 0 ,0
Exp/Cntr=0.3,0.1

Type RM Length L Ch R = 1 ,650     ,0,0,0
BEGIN DESCRIPTION:
Mapping XS 70ddec1d
END DESCRIPTION:
XS GIS Cut Line= 3
      1686150.27      7040279.11      1685360.93      7041590.24
      1685969.33      7042312.16
#Sta/Elev= 30
  3469.6 1502.74  3720.7 1473.34  3975.1 1466.42  4223.7 1449.23  4411.9 1443.97
  4462.6 1440.44  4536.4 1406.27  4551.9  1402.1  4557.8 1406.31  4573.3 1393.65
  4610.2 1380.36  4652.9    1379  4689.8 1367.03  4732.6 1365.16  4853.5 1344.91
  4915.7 1333.14  4944.2 1340.84  4965.6 1333.83  4984.6 1316.56  4985.1 1316.06
    5007 1316.56  5079.1 1320.22  5150.6 1338.33  5185.7 1328.57  5278.1 1325.21
  5327.5 1334.15    5399 1357.81  5547.3 1383.92  5652.6  1392.9  5944.1 1402.99
#Mann= 6 ,-1 , 0
  3469.6     .07       0  4411.9     .16       0  4853.5     .07       0
  4984.6     .07       0    5007     .07       0  5652.6     .16       0
Bank Sta=4984.6,5007
XS Rating Curve= 0 ,0
Exp/Cntr=0.3,0.1

Chan Stop Cuts=-1
Use User Specified Reach Order=0
Composite Channel Slope=5