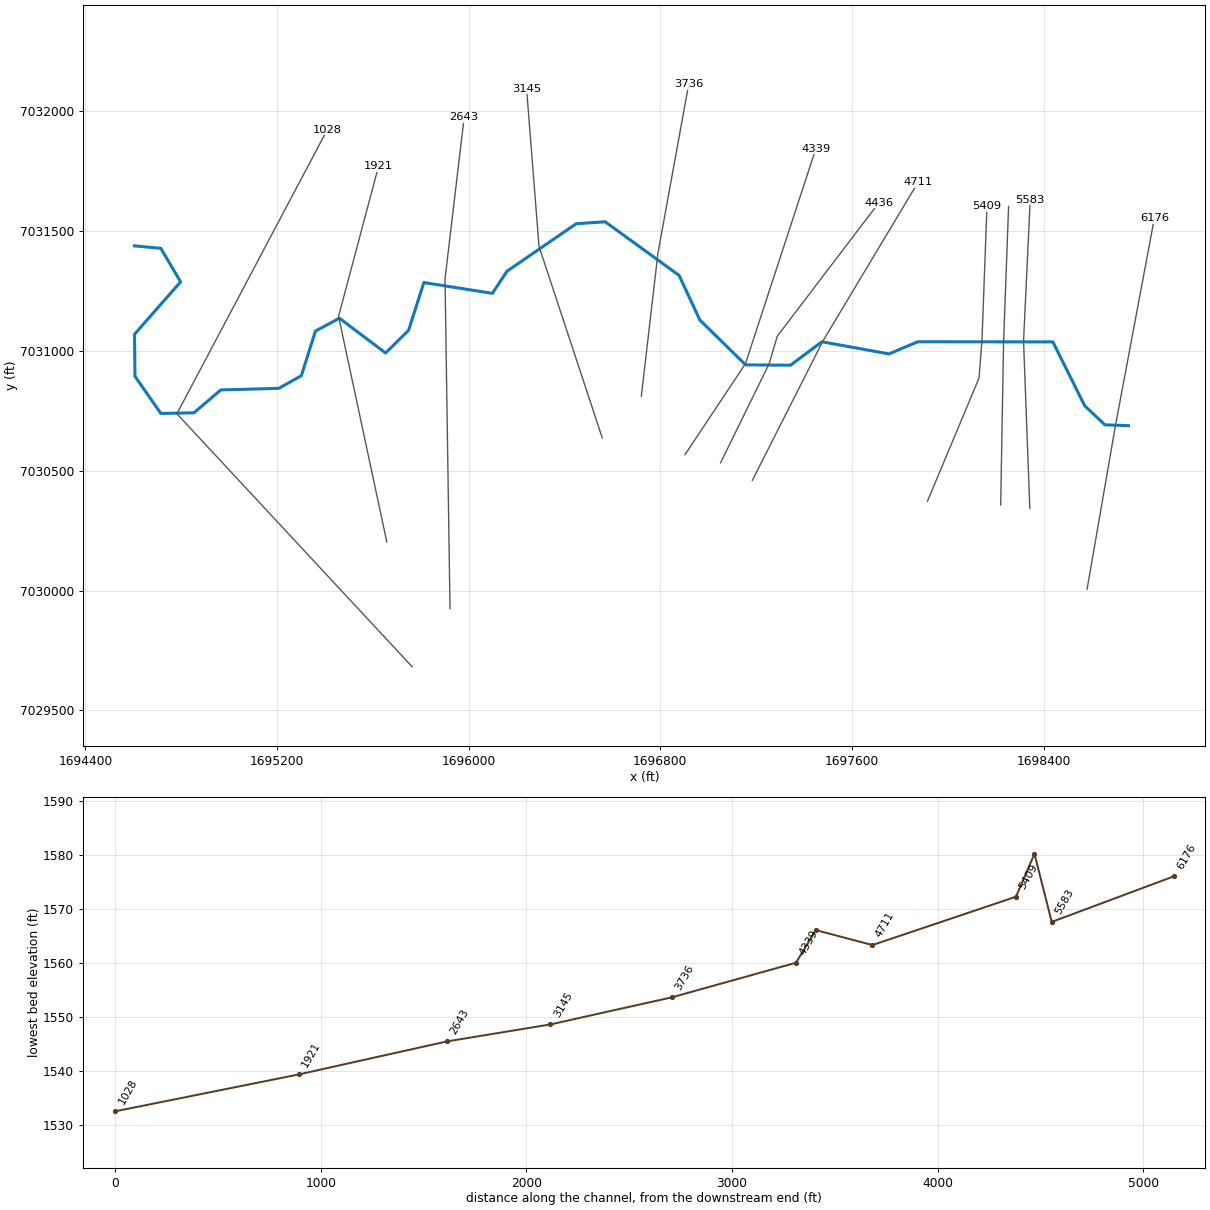
--- Chimney Creek 1191.prj (project) ---

Proj Title=Chimney Creek 1191 Base Level Engineering
Current Plan=p01
Default Exp/Contr=0.3,0.1
English Units
Geom File=g01
Flow File=f01
Plan File=p01
BEGIN DESCRIPTION:
Chimney Creek 1191
END DESCRIPTION:

--- Chimney Creek 1191.p01 (plan) ---

Plan Title=Multiple Run
Short Identifier=Multiple
Geom File=g01
Flow File=f01
Subcritical Flow
K Sum by GR= 0
Std Step Tol= 0.01
Critical Tol= 0.01
Num of Std Step Trials= 20
Max Error Tol= 0.3
Flow Tol Ratio= 0.001
Split Flow NTrial= 30
Split Flow Tol= 0.02
Split Flow Ratio= 0.02
Log Output Level= 0
Friction Slope Method= 1
Unsteady Friction Slope Method= 2
Unsteady Bridges Friction Slope Method= 1
Parabolic Critical Depth
Global Vel Dist=  1 , 1 , 1
Global Log Level= 0
CheckData=True
Encroach Param= -1, 0, 0, 0
BEGIN DESCRIPTION:
Multiple Run
END DESCRIPTION:

--- Chimney Creek 1191.f01 (steady flow) ---

Flow Title=Multiple
Number of Profiles=7
Profile Names=10-year,25-year,50-year,1pct_min,100-year,1pct_plu,500-year
River Rch & RM= Chimney Creek 11,Reach-1,6176
     315     444     554     344     687    1370    1069
River Rch & RM= Chimney Creek 11,Reach-1,5583
     396     563     706     441     879    1754    1382
Boundary for River Rch & Prof#=Chimney Creek 11,Reach-1,1
Up Type=0
Dn Type=3
Dn Slope=0.005
Boundary for River Rch & Prof#=Chimney Creek 11,Reach-1,2
Up Type=0
Dn Type=3
Dn Slope=0.005
Boundary for River Rch & Prof#=Chimney Creek 11,Reach-1,3
Up Type=0
Dn Type=3
Dn Slope=0.005
Boundary for River Rch & Prof#=Chimney Creek 11,Reach-1,4
Up Type=0
Dn Type=3
Dn Slope=0.005
Boundary for River Rch & Prof#=Chimney Creek 11,Reach-1,5
Up Type=0
Dn Type=3
Dn Slope=0.005
Boundary for River Rch & Prof#=Chimney Creek 11,Reach-1,6
Up Type=0
Dn Type=3
Dn Slope=0.005
Boundary for River Rch & Prof#=Chimney Creek 11,Reach-1,7
Up Type=0
Dn Type=3
Dn Slope=0.005

--- Chimney Creek 1191.g01 (geometry) ---

Geom Title=Existing Conditions

River Reach=Chimney Creek 11,Reach-1
Reach XY= 30
      1698755.00      7030688.00      1698656.39      7030691.38
      1698571.63      7030771.29      1698439.18      7031037.34
      1697875.03      7031037.93      1697755.00      7030987.18
      1697475.01      7031037.94      1697343.73      7030940.15
      1697156.47      7030941.53      1696965.76      7031128.32
      1696878.71      7031314.82      1696570.17      7031538.48
      1696448.82      7031530.18      1696160.63      7031332.35
      1696099.28      7031239.91      1695813.28      7031284.95
      1695749.48      7031085.56      1695653.34      7030991.08
      1695460.73      7031136.15      1695360.58      7031082.43
      1695301.85      7030896.31      1695207.39      7030843.69
      1694965.44      7030836.94      1694853.53      7030741.54
      1694715.29      7030738.97      1694607.24      7030893.93
      1694605.47      7031069.33      1694797.72      7031287.91
      1694715.18      7031427.71      1694605.00      7031438.00

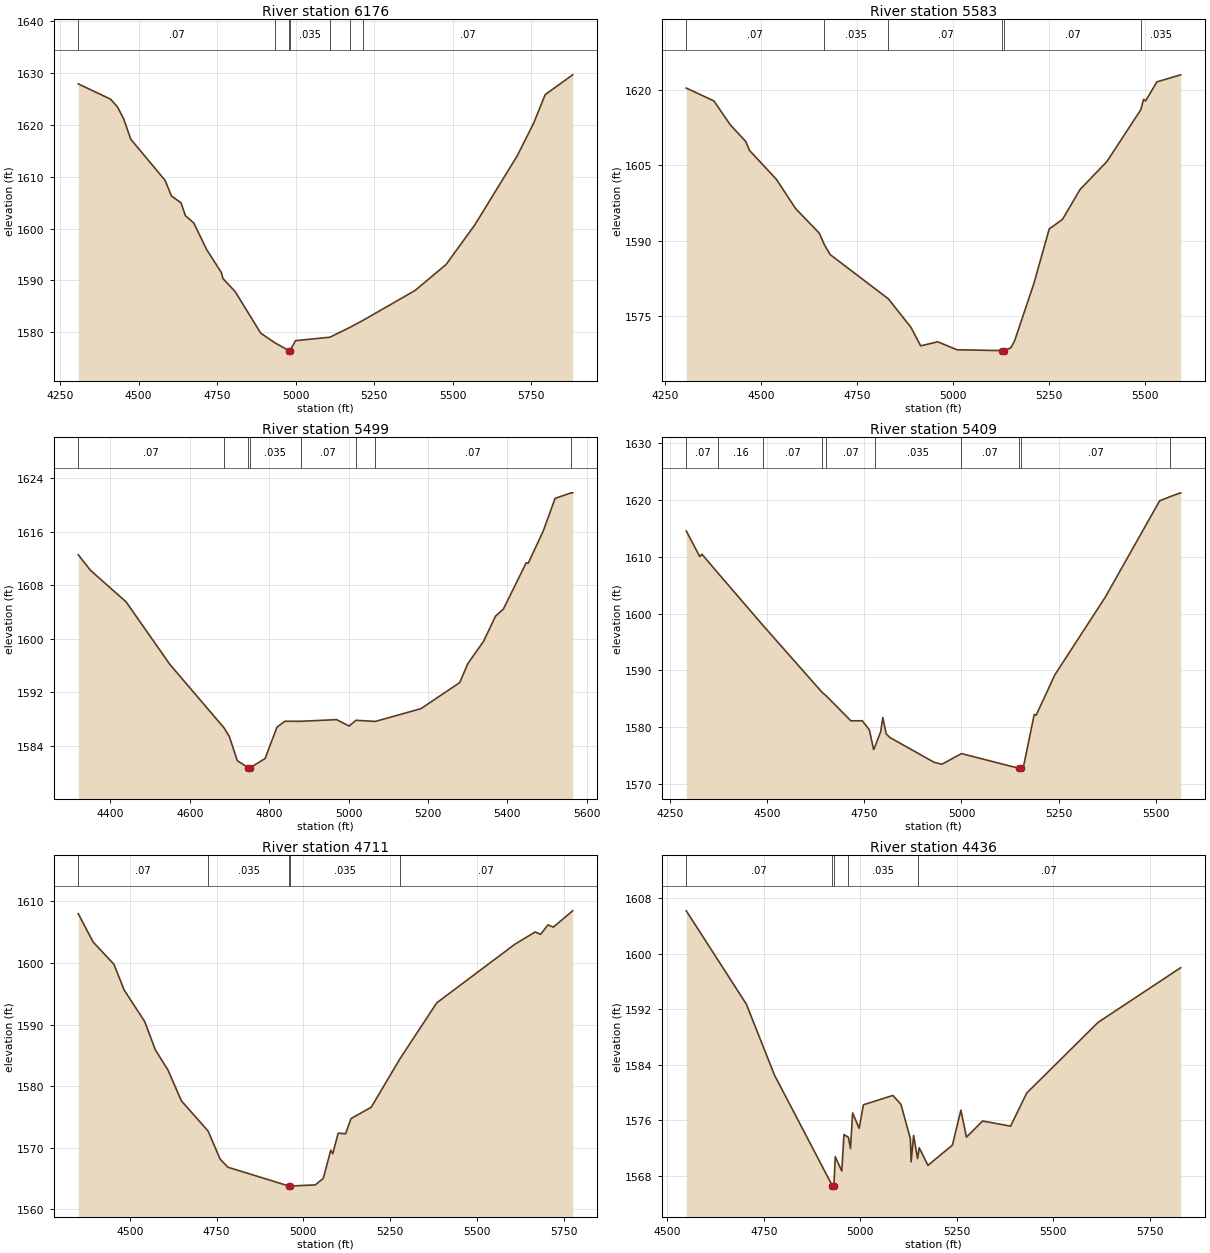
Type RM Length L Ch R = 1,6176,593,593,593
BEGIN DESCRIPTION:
Chimney Creek 1191 11.0
END DESCRIPTION:
XS GIS Cut Line= 3
      1698581.94      7030005.62      1698700.14      7030687.25
      1698863.00      7031554.08
#Sta/Elev= 30
  4308.2 1627.87  4410.5 1624.94  4432.4 1623.49  4452.7 1621.14  4475.3 1617.21
  4584.5 1609.29  4604.9 1606.28  4635.4 1604.95  4649.3 1602.47  4676.0 1601.07
  4716.6 1595.99  4763.7 1591.52  4768.7 1590.37  4807.9 1587.84  4889.1 1579.84
  4934.9 1577.96  4978.5 1576.50  4978.7 1576.00  4982.5 1576.50  4999.6 1578.40
  5109.4 1579.07  5174.0 1580.99  5215.2 1582.33  5380.3 1588.07  5479.0 1593.07
  5570.6 1600.71  5705.6 1614.02  5758.1 1620.34  5794.4 1625.79  5882.0 1629.61
#Mann=7,-1,0
  4308.2    0.07       0  4934.9   0.035       0  4978.5   0.035       0
  4982.5   0.035       0  5109.4    0.07       0  5174.0   0.035       0
  5215.2    0.07       0
Bank Sta=4978.5,4982.5
Exp/Cntr=0.3,0.1

Type RM Length L Ch R = 1,5583,84,84,84
BEGIN DESCRIPTION:
Mapping XS 8fbc2ce7
END DESCRIPTION:
XS GIS Cut Line= 3
      1698342.79      7030343.51      1698316.74      7031041.47
      1698344.52      7031629.97
#Sta/Elev= 30
  4305.0 1620.40  4377.1 1617.83  4419.6 1613.08  4459.6 1609.78  4469.6 1607.98
  4539.7 1602.22  4589.7 1596.39  4651.3 1591.50  4664.2 1589.26  4679.7 1587.22
  4831.3 1578.40  4889.9 1572.74  4915.5 1569.03  4959.9 1569.84  5010.0 1568.25
  5128.1 1568.08  5128.4 1567.58  5132.2 1568.08  5150.1 1568.61  5160.1 1570.04
  5210.2 1581.44  5250.2 1592.32  5285.0 1594.26  5330.3 1600.17  5400.4 1605.76
  5488.8 1616.10  5496.1 1618.17  5501.1 1617.83  5530.6 1621.64  5592.6 1623.04
#Mann=6,-1,0
  4305.0    0.07       0  4664.2   0.035       0  4831.3    0.07       0
  5128.1    0.07       0  5132.2    0.07       0  5488.8   0.035       0
Bank Sta=5128.1,5132.2
Exp/Cntr=0.3,0.1

Type RM Length L Ch R = 1,5499,90,90,90
BEGIN DESCRIPTION:
Mapping XS eebc4595
END DESCRIPTION:
XS GIS Cut Line= 3
      1698221.26      7030357.43      1698233.41      7031039.73
      1698254.24      7031602.24
#Sta/Elev= 30
  4319.3 1612.57  4349.9 1610.25  4439.9 1605.51  4549.9 1596.17  4686.7 1586.64
  4699.9 1585.35  4719.9 1581.74  4747.9 1580.68  4748.2 1580.18  4752.0 1580.68
  4789.9 1582.07  4819.9 1586.77  4839.9 1587.65  4879.3 1587.64  4970.0 1587.89
  5001.7 1586.93  5018.6 1587.79  5067.5 1587.62  5182.4 1589.53  5280.2 1593.44
  5300.2 1596.24  5340.2 1599.62  5370.2 1603.37  5390.2 1604.45  5447.6 1611.37
  5452.6 1611.30  5490.3 1616.10  5520.3 1621.01  5560.9 1621.84  5564.6 1621.84
#Mann=8,-1,0
  4319.3    0.07       0  4686.7   0.035       0  4747.9    0.07       0
  4752.0   0.035       0  4879.3    0.07       0  5018.6   0.035       0
  5067.5    0.07       0  5560.9   0.035       0
Bank Sta=4747.9,4752
Exp/Cntr=0.3,0.1

Type RM Length L Ch R = 1,5409,698,698,698
BEGIN DESCRIPTION:
Mapping XS 54ba4f8d
END DESCRIPTION:
XS GIS Cut Line= 4
      1697915.70      7030373.05      1698130.98      7030886.95
      1698143.13      7031043.20      1698163.96      7031602.22
#Sta/Elev= 30
  4291.3 1614.58  4326.0 1610.05  4331.5 1610.49  4373.9 1607.08  4488.4 1597.97
  4640.9 1586.14  4652.3 1585.47  4715.3 1581.10  4744.5 1581.12  4762.9 1579.52
  4773.7 1576.06  4776.1 1576.35  4792.1 1579.23  4797.5 1581.69  4806.2 1578.79
  4815.9 1578.16  4929.8 1573.79  4949.8 1573.46  5000.0 1575.33  5148.0 1572.74
  5148.3 1572.24  5152.1 1572.74  5160.1 1573.15  5187.4 1582.23  5192.4 1582.10
  5240.2 1589.18  5370.2 1602.89  5510.3 1619.89  5538.2 1620.65  5564.6 1621.30
#Mann=10,-1,0
  4291.3    0.07       0  4373.9    0.16       0  4488.4    0.07       0
  4640.9   0.035       0  4652.3    0.07       0  4776.1   0.035       0
  5000.0    0.07       0  5148.0    0.07       0  5152.1    0.07       0
  5538.2   0.035       0
Bank Sta=5148,5152.1
Exp/Cntr=0.3,0.1

Type RM Length L Ch R = 1,4711,275,275,275
BEGIN DESCRIPTION:
Mapping XS fb4e0af6
END DESCRIPTION:
XS GIS Cut Line= 3
      1697184.57      7030459.80      1697478.85      7031040.54
      1697876.79      7031703.77
#Sta/Elev= 30
  4351.7 1608.01  4394.5 1603.41  4454.2 1599.81  4484.2 1595.60  4543.3 1590.48
  4573.9 1585.89  4610.1 1582.64  4649.0 1577.62  4725.8 1572.73  4760.4 1568.18
  4782.7 1566.86  4958.8 1563.80  4959.1 1563.30  4962.9 1563.80  5034.8 1563.99
  5057.8 1565.06  5079.2 1569.62  5085.0 1569.05  5100.5 1572.38  5121.9 1572.29
  5137.5 1574.75  5195.8 1576.59  5278.3 1584.43  5384.6 1593.54  5609.8 1603.05
  5668.1 1605.04  5683.6 1604.65  5705.0 1606.18  5720.6 1605.83  5776.2 1608.47
#Mann=5,-1,0
  4351.7    0.07       0  4725.8   0.035       0  4958.8   0.035       0
  4962.9   0.035       0  5278.3    0.07       0
Bank Sta=4958.8,4962.9
Exp/Cntr=0.3,0.1

Type RM Length L Ch R = 1,4436,97,97,97
BEGIN DESCRIPTION:
Mapping XS 33d3ece4
END DESCRIPTION:
XS GIS Cut Line= 4
      1697051.77      7030532.73      1697254.89      7030946.79
      1697288.75      7031061.37      1697713.21      7031618.65
#Sta/Elev= 30
  4548.8 1606.15  4704.4 1592.72  4777.4 1582.49  4927.2 1566.57  4927.4 1566.07
  4931.4 1566.57  4934.9 1570.75  4951.8 1568.66  4957.4 1573.93  4969.0 1573.53
  4974.3 1571.92  4979.8 1577.04  4996.8 1574.83  5007.9 1578.22  5084.3 1579.56
  5105.1 1578.27  5129.5 1573.33  5131.5 1569.99  5137.8 1573.80  5148.2 1570.47
  5152.4 1572.03  5175.1 1569.49  5238.4 1572.41  5260.4 1577.44  5274.9 1573.56
  5316.6 1575.88  5389.2 1575.14  5430.9 1579.90  5616.0 1590.09  5830.0 1597.96
#Mann=5,-1,0
  4548.8    0.07       0  4927.2   0.035       0  4931.4    0.07       0
  4969.0   0.035       0  5148.2    0.07       0
Bank Sta=4927.2,4931.4
Exp/Cntr=0.3,0.1

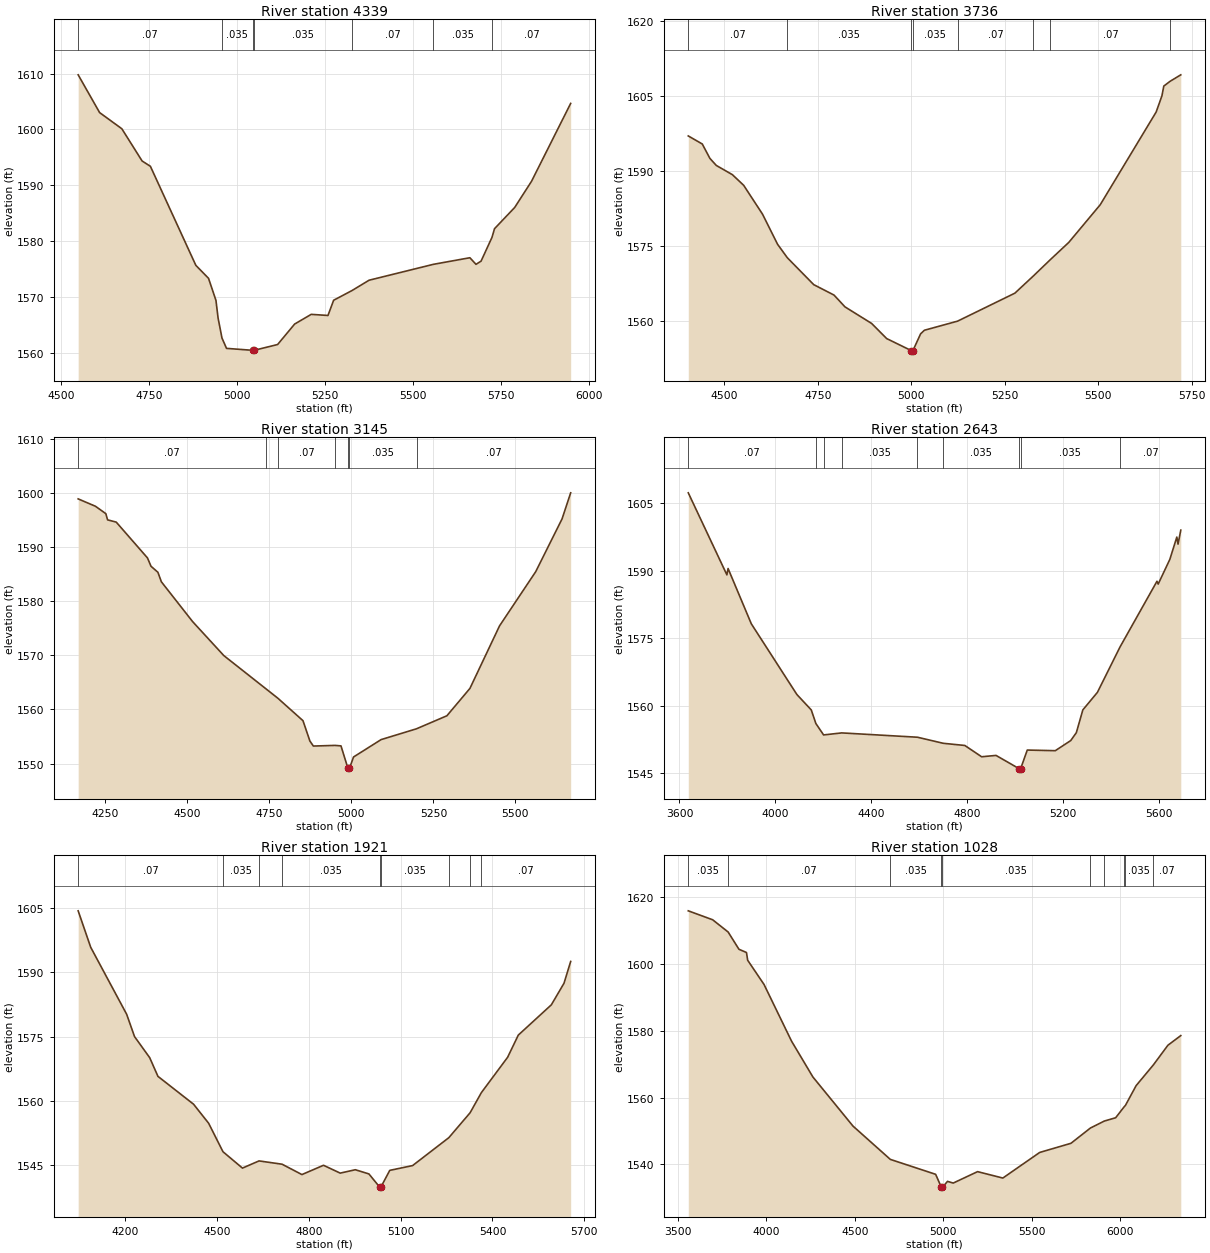
Type RM Length L Ch R = 1,4339,603,603,603
BEGIN DESCRIPTION:
Mapping XS 44965b34
END DESCRIPTION:
XS GIS Cut Line= 3
      1696903.30      7030566.54      1697155.93      7030946.79
      1697449.73      7031843.78
#Sta/Elev= 30
  4548.0 1609.77  4609.0 1603.02  4672.2 1600.13  4729.8 1594.37  4753.4 1593.42
  4882.6 1575.72  4918.7 1573.40  4939.8 1569.45  4945.9 1566.29  4956.9 1562.73
  4969.8 1560.88  5044.1 1560.53  5044.3 1560.03  5048.3 1560.53  5115.1 1561.57
  5163.6 1565.23  5210.7 1566.96  5258.3 1566.76  5274.4 1569.48  5326.5 1571.21
  5375.2 1573.06  5558.0 1575.90  5661.8 1577.08  5679.2 1575.90  5693.6 1576.47
  5724.6 1580.71  5731.9 1582.27  5789.2 1586.06  5837.1 1590.74  5948.4 1604.66
#Mann=7,-1,0
  4548.0    0.07       0  4956.9   0.035       0  5044.1   0.035       0
  5048.3   0.035       0  5326.5    0.07       0  5558.0   0.035       0
  5724.6    0.07       0
Bank Sta=5044.1,5048.3
Exp/Cntr=0.3,0.1

Type RM Length L Ch R = 1,3736,591,591,591
BEGIN DESCRIPTION:
Mapping XS e74485e7
END DESCRIPTION:
XS GIS Cut Line= 3
      1696721.09      7030810.71      1696790.54      7031407.96
      1696919.02      7032112.87
#Sta/Elev= 30
  4403.3 1597.03  4440.8 1595.42  4461.0 1592.56  4478.2 1591.14  4521.4 1589.29
  4551.6 1587.16  4601.9 1581.41  4642.2 1575.39  4668.4 1572.69  4739.0 1567.32
  4793.2 1565.24  4822.6 1562.88  4893.9 1559.57  4934.1 1556.55  5000.1 1554.14
  5000.3 1553.64  5004.4 1554.14  5024.9 1557.49  5035.1 1558.21  5123.9 1560.03
  5277.2 1565.62  5326.0 1569.01  5372.4 1572.34  5421.4 1575.76  5505.6 1583.29
  5655.2 1601.81  5670.6 1605.04  5675.7 1607.00  5692.8 1607.96  5721.1 1609.24
#Mann=8,-1,0
  4403.3    0.07       0  4668.4   0.035       0  5000.1   0.035       0
  5004.4   0.035       0  5123.9    0.07       0  5326.0   0.035       0
  5372.4    0.07       0  5692.8   0.035       0
Bank Sta=5000.1,5004.4
Exp/Cntr=0.3,0.1

Type RM Length L Ch R = 1,3145,502,502,502
BEGIN DESCRIPTION:
Mapping XS 6dcedefd
END DESCRIPTION:
XS GIS Cut Line= 3
      1696557.90      7030637.14      1696294.01      7031435.74
      1696242.03      7032094.22
#Sta/Elev= 30
  4167.0 1598.89  4219.7 1597.53  4251.4 1596.16  4256.7 1595.02  4283.1 1594.60
  4378.3 1587.99  4389.1 1586.45  4410.1 1585.34  4420.7 1583.58  4515.8 1576.24
  4611.0 1569.96  4739.3 1563.83  4775.9 1562.08  4852.5 1557.93  4873.5 1554.18
  4884.1 1553.25  4950.0 1553.37  4968.3 1553.28  4989.6 1549.12  4989.9 1548.62
  4994.0 1549.12  5006.6 1551.23  5090.6 1554.44  5198.7 1556.44  5291.2 1558.84
  5361.4 1563.89  5451.7 1575.44  5562.0 1585.45  5642.3 1595.19  5668.6 1600.01
#Mann=7,-1,0
  4167.0    0.07       0  4739.3   0.035       0  4775.9    0.07       0
  4950.0   0.035       0  4989.6   0.035       0  4994.0   0.035       0
  5198.7    0.07       0
Bank Sta=4989.6,4994
Exp/Cntr=0.3,0.1

Type RM Length L Ch R = 1,2643,722,722,722
BEGIN DESCRIPTION:
Mapping XS b79c39fa
END DESCRIPTION:
XS GIS Cut Line= 3
      1695922.49      7029925.35      1695901.65      7031300.32
      1695981.46      7031973.48
#Sta/Elev= 30
  3636.7 1607.31  3797.6 1589.09  3802.6 1590.50  3899.4 1578.22  4089.4 1562.51
  4149.4 1559.08  4168.6 1556.06  4200.8 1553.53  4276.5 1553.98  4592.1 1553.02
  4699.8 1551.67  4789.5 1551.19  4859.5 1548.68  4919.5 1548.98  5017.3 1545.99
  5017.7 1545.49  5021.8 1545.99  5049.8 1550.17  5166.6 1550.03  5231.0 1552.28
  5254.4 1554.04  5281.4 1559.09  5342.2 1562.99  5436.5 1573.08  5590.4 1587.66
  5595.5 1587.04  5643.9 1592.51  5673.2 1597.48  5678.2 1595.91  5689.7 1599.02
#Mann=9,-1,0
  3636.7    0.07       0  4168.6   0.035       0  4200.8    0.07       0
  4276.5   0.035       0  4592.1    0.07       0  4699.8   0.035       0
  5017.3   0.035       0  5021.8   0.035       0  5436.5    0.07       0
Bank Sta=5017.3,5021.8
Exp/Cntr=0.3,0.1

Type RM Length L Ch R = 1,1921,893,893,893
BEGIN DESCRIPTION:
Mapping XS 1c4e4d3d
END DESCRIPTION:
XS GIS Cut Line= 3
      1695658.61      7030203.06      1695457.21      7031144.07
      1695623.88      7031769.10
#Sta/Elev= 30
  4046.4 1604.38  4087.4 1595.86  4204.9 1580.21  4230.6 1575.00  4280.1 1570.08
  4307.1 1565.71  4423.4 1559.21  4472.8 1554.75  4519.5 1548.11  4583.2 1544.28
  4637.3 1545.96  4712.7 1545.19  4777.5 1542.77  4848.0 1544.94  4902.6 1543.11
  4952.0 1543.90  4996.4 1542.92  5031.2 1539.87  5031.5 1539.37  5035.7 1539.87
  5064.5 1543.75  5139.1 1544.87  5257.5 1551.39  5327.0 1557.21  5363.9 1561.92
  5449.6 1570.17  5484.5 1575.35  5592.4 1582.42  5633.8 1587.46  5655.6 1592.55
#Mann=9,-1,0
  4046.4    0.07       0  4519.5   0.035       0  4637.3    0.07       0
  4712.7   0.035       0  5031.2   0.035       0  5035.7   0.035       0
  5257.5    0.07       0  5327.0   0.035       0  5363.9    0.07       0
Bank Sta=5031.2,5035.7
Exp/Cntr=0.3,0.1

Type RM Length L Ch R = 1,1028,0,0,0
BEGIN DESCRIPTION:
Chimney Creek 1191 1.0
END DESCRIPTION:
XS GIS Cut Line= 3
      1695764.16      7029682.60      1694782.28      7030737.57
      1695410.01      7031922.24
#Sta/Elev= 30
  3558.8 1615.95  3696.5 1613.27  3784.0 1609.60  3845.0 1604.43  3887.5 1603.46
  3894.3 1601.14  3986.7 1593.88  4142.1 1576.90  4262.8 1566.15  4489.0 1551.45
  4700.1 1541.46  4956.0 1536.99  4988.7 1533.05  4989.1 1532.55  4993.7 1533.05
  5023.1 1534.87  5055.3 1534.37  5192.9 1537.79  5335.6 1535.87  5543.7 1543.54
  5720.2 1546.28  5830.3 1550.86  5908.7 1552.95  5972.8 1553.94  6021.1 1557.24
  6028.2 1557.66  6088.5 1563.57  6185.9 1569.78  6268.0 1575.67  6340.7 1578.56
#Mann=10,-1,0
  3558.8   0.035       0  3784.0    0.07       0  4700.1   0.035       0
  4988.7   0.035       0  4993.7   0.035       0  5830.3    0.07       0
  5908.7   0.035       0  6021.1    0.07       0  6028.2   0.035       0
  6185.9    0.07       0
Bank Sta=4988.7,4993.7
Exp/Cntr=0.3,0.1

Chan Stop Cuts=-1