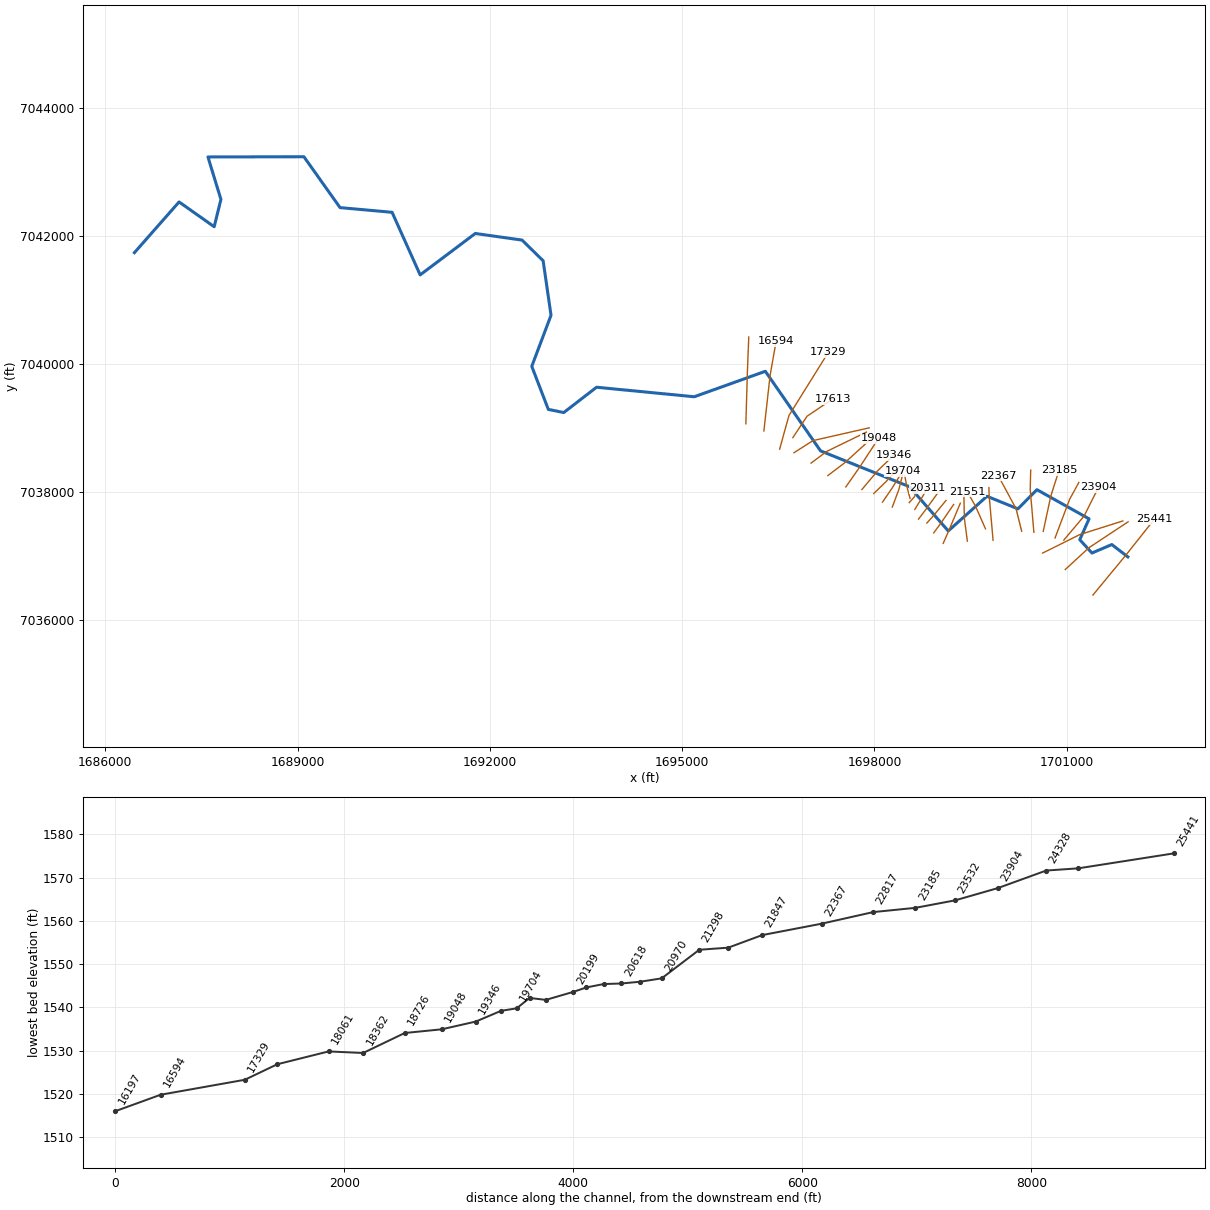
--- Chimney Creek 1192.prj (project) ---

Proj Title=Chimney Creek 1192 Base Level Engineering
Current Plan=p01
Default Exp/Contr=0.3,0.1
English Units
Geom File=g01
Flow File=f01
Plan File=p01
BEGIN DESCRIPTION:
Chimney Creek 1192
END DESCRIPTION:

--- Chimney Creek 1192.p01 (plan) ---

Plan Title=Multiple Run
Short Identifier=Multiple
Geom File=g01
Flow File=f01
Subcritical Flow
K Sum by GR= 0
Std Step Tol= 0.01
Critical Tol= 0.01
Num of Std Step Trials= 20
Max Error Tol= 0.3
Flow Tol Ratio= 0.001
Split Flow NTrial= 30
Split Flow Tol= 0.02
Split Flow Ratio= 0.02
Log Output Level= 0
Friction Slope Method= 1
Unsteady Friction Slope Method= 2
Unsteady Bridges Friction Slope Method= 1
Parabolic Critical Depth
Global Vel Dist=  1 , 1 , 1
Global Log Level= 0
CheckData=True
Encroach Param= -1, 0, 0, 0
BEGIN DESCRIPTION:
Multiple Run
END DESCRIPTION:

--- Chimney Creek 1192.f01 (steady flow) ---

Flow Title=Multiple
Number of Profiles=7
Profile Names=10-year,25-year,50-year,1pct_min,100-year,1pct_plu,500-year
River Rch & RM= Chimney Creek 11,Reach-1,25441
     273     376     462     283     564    1125     850
River Rch & RM= Chimney Creek 11,Reach-1,23904
     311     432     532     327     652    1301     991
River Rch & RM= Chimney Creek 11,Reach-1,19346
     455     646     807     502    1002    1999    1562
River Rch & RM= Chimney Creek 11,Reach-1,17613
     572     821    1033     646    1289    2572    2033
River Rch & RM= Chimney Creek 11,Reach-1,9335
     706    1025    1302     822    1640    3271    2633
Boundary for River Rch & Prof#=Chimney Creek 11,Reach-1,1
Up Type=0
Dn Type=3
Dn Slope=0.005
Boundary for River Rch & Prof#=Chimney Creek 11,Reach-1,2
Up Type=0
Dn Type=3
Dn Slope=0.005
Boundary for River Rch & Prof#=Chimney Creek 11,Reach-1,3
Up Type=0
Dn Type=3
Dn Slope=0.005
Boundary for River Rch & Prof#=Chimney Creek 11,Reach-1,4
Up Type=0
Dn Type=3
Dn Slope=0.005
Boundary for River Rch & Prof#=Chimney Creek 11,Reach-1,5
Up Type=0
Dn Type=3
Dn Slope=0.005
Boundary for River Rch & Prof#=Chimney Creek 11,Reach-1,6
Up Type=0
Dn Type=3
Dn Slope=0.005
Boundary for River Rch & Prof#=Chimney Creek 11,Reach-1,7
Up Type=0
Dn Type=3
Dn Slope=0.005

--- Chimney Creek 1192.g01 (geometry) ---

Geom Title=Existing Conditions

River Reach=Chimney Creek 11,Reach-1
Reach XY= 30
      1701955.00      7036988.00      1701704.76      7037181.03
      1701395.02      7037048.68      1701205.07      7037256.22
      1701349.90      7037582.53      1700536.31      7038037.50
      1700239.79      7037738.24      1699756.76      7037934.70
      1699152.78      7037393.30      1698546.59      7038084.72
      1697160.47      7038643.26      1696299.12      7039886.04
      1695189.84      7039488.37      1693665.43      7039636.95
      1693153.50      7039241.46      1692913.02      7039291.31
      1692654.80      7039962.92      1692954.99      7040760.76
      1692832.12      7041611.52      1692503.50      7041934.39
      1691773.58      7042037.75      1690913.34      7041390.97
      1690475.39      7042368.15      1689663.44      7042441.40
      1689099.16      7043235.95      1687602.41      7043232.29
      1687804.79      7042569.73      1687699.53      7042143.10
      1687151.68      7042529.96      1686455.00      7041738.00

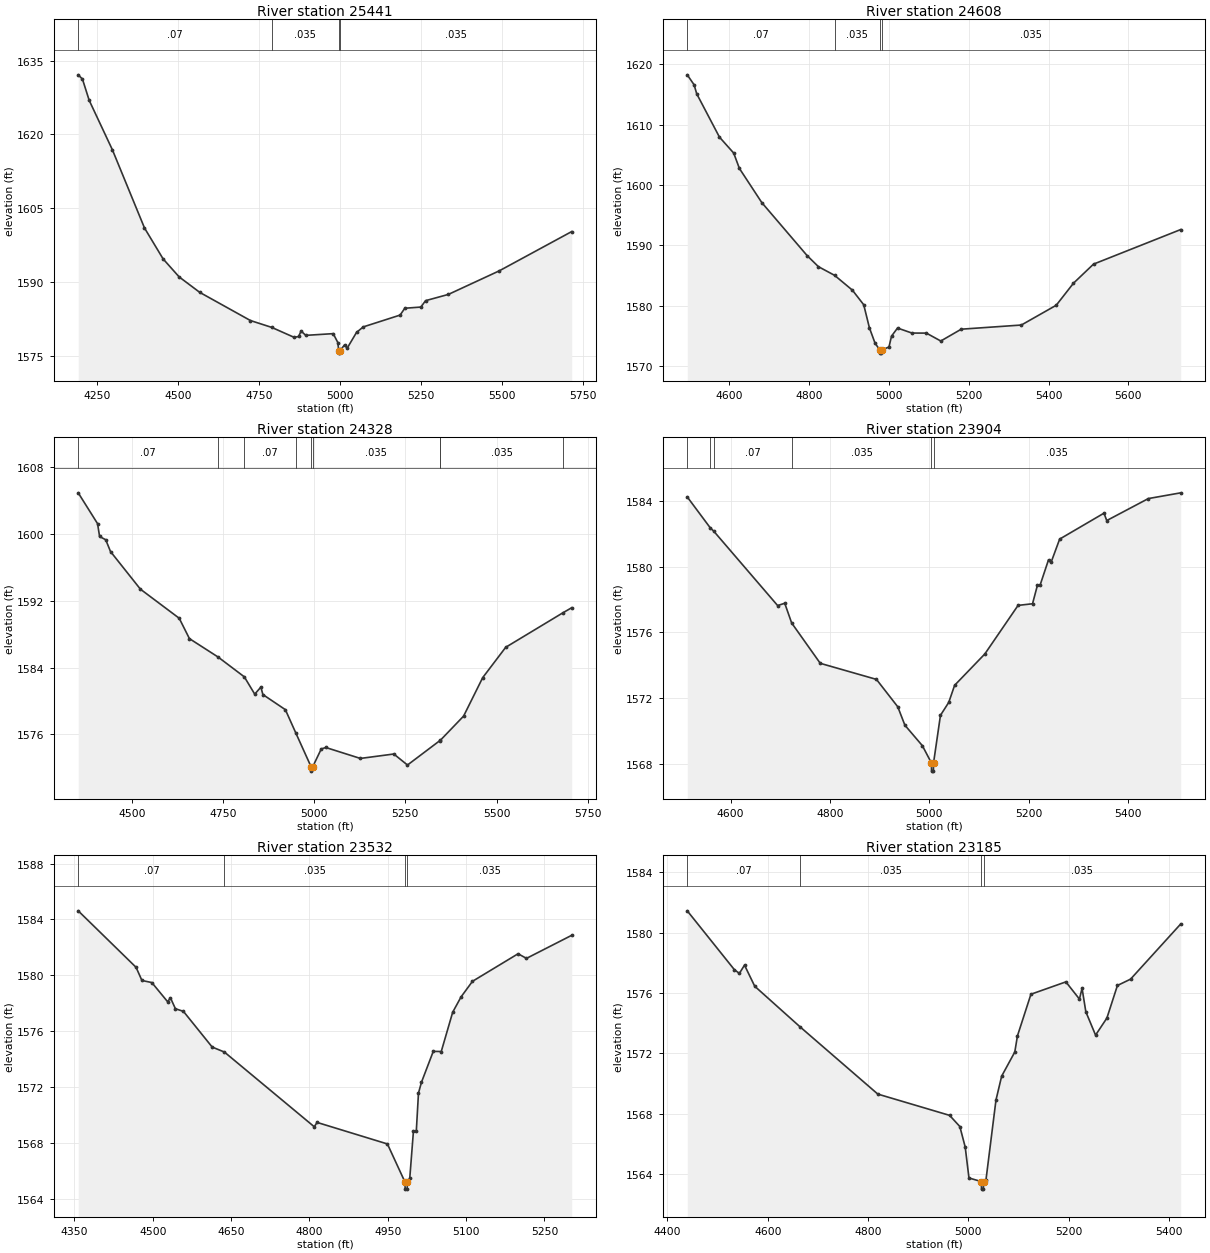
Type RM Length L Ch R = 1,25441,833,833,833
BEGIN DESCRIPTION:
Chimney Creek 1192 52.0
END DESCRIPTION:
XS GIS Cut Line= 3
      1701411.22      7036393.43      1701925.91      7037017.85
      1702369.53      7037577.44
#Sta/Elev= 30
  4190.8 1632.12  4203.9 1631.25  4224.7 1626.93  4296.4 1616.87  4395.4 1601.00
  4452.8 1594.72  4502.3 1591.06  4566.1 1587.91  4722.5 1582.19  4788.1 1580.80
  4857.6 1578.77  4871.0 1578.95  4878.9 1580.05  4893.2 1579.18  4977.9 1579.53
  4992.2 1577.72  4994.9 1576.07  4995.1 1575.57  4998.9 1576.07  5013.0 1577.25
  5021.0 1576.57  5049.9 1579.78  5070.7 1580.90  5184.4 1583.30  5198.9 1584.69
  5248.5 1584.93  5263.0 1586.23  5333.4 1587.50  5490.5 1592.29  5714.1 1600.27
#Mann=4,-1,0
  4190.8    0.07       0  4788.1   0.035       0  4994.9   0.035       0
  4998.9   0.035       0
Bank Sta=4994.9,4998.9
Exp/Cntr=0.3,0.1

Type RM Length L Ch R = 1,24608,280,280,280
BEGIN DESCRIPTION:
Mapping XS 95939f34
END DESCRIPTION:
XS GIS Cut Line= 3
      1700978.16      7036790.81      1701349.68      7037132.82
      1701959.03      7037535.58
#Sta/Elev= 30
  4495.6 1618.28  4512.7 1616.63  4519.4 1615.12  4576.2 1607.95  4611.9 1605.30
  4626.1 1602.76  4682.2 1597.09  4795.6 1588.30  4824.0 1586.46  4864.5 1585.02
  4909.1 1582.56  4937.4 1580.14  4951.6 1576.32  4965.8 1573.76  4978.0 1572.62
  4978.2 1572.12  4981.7 1572.12  4982.0 1572.62  5000.6 1573.14  5007.0 1574.94
  5022.0 1576.28  5058.1 1575.45  5094.2 1575.44  5130.3 1574.13  5181.5 1576.09
  5332.0 1576.78  5419.3 1580.06  5462.5 1583.72  5512.6 1586.88  5731.0 1592.62
#Mann=4,-1,0
  4495.6    0.07       0  4864.5   0.035       0  4978.0   0.035       0
  4982.0   0.035       0
Bank Sta=4978,4982
Exp/Cntr=0.3,0.1

Type RM Length L Ch R = 1,24328,424,424,424
BEGIN DESCRIPTION:
Mapping XS 5277d9c2
END DESCRIPTION:
XS GIS Cut Line= 3
      1700625.76      7037047.77      1701203.85      7037335.95
      1701877.47      7037549.49
#Sta/Elev= 30
  4353.4 1604.94  4406.4 1601.25  4412.0 1599.71  4428.8 1599.32  4441.9 1597.91
  4523.9 1593.40  4630.2 1589.92  4658.2 1587.48  4736.6 1585.28  4808.7 1582.90
  4837.2 1580.83  4854.0 1581.67  4859.6 1580.78  4921.2 1578.97  4949.5 1576.21
  4991.9 1572.11  4992.1 1571.61  4995.9 1572.11  5019.5 1574.26  5032.0 1574.44
  5126.8 1573.13  5218.4 1573.66  5255.9 1572.34  5344.2 1575.25  5345.9 1575.30
  5409.7 1578.20  5462.1 1582.81  5525.1 1586.44  5681.4 1590.56  5706.0 1591.18
#Mann=9,-1,0
  4353.4    0.07       0  4736.6   0.035       0  4808.7    0.07       0
  4949.5   0.035       0  4991.9   0.035       0  4995.9   0.035       0
  5344.2    0.07       0  5345.9   0.035       0  5681.4    0.07       0
Bank Sta=4991.9,4995.9
Exp/Cntr=0.3,0.1

Type RM Length L Ch R = 1,23904,372,372,372
BEGIN DESCRIPTION:
Mapping XS 3e1317ec
END DESCRIPTION:
XS GIS Cut Line= 3
      1700955.93      7037250.17      1701270.62      7037623.46
      1701497.74      7038074.46
#Sta/Elev= 30
  4512.7 1584.25  4558.9 1582.37  4566.1 1582.16  4694.6 1577.63  4708.9 1577.77
  4722.8 1576.57  4780.4 1574.11  4893.5 1573.13  4936.4 1571.46  4950.7 1570.34
  4985.9 1569.09  5004.1 1568.04  5004.4 1567.54  5008.1 1567.54  5008.4 1568.04
  5022.3 1570.94  5039.0 1571.73  5050.8 1572.77  5111.6 1574.68  5178.5 1577.64
  5207.6 1577.74  5217.5 1578.87  5223.1 1578.90  5239.8 1580.42  5245.4 1580.30
  5262.2 1581.68  5351.4 1583.26  5357.0 1582.81  5440.7 1584.15  5505.9 1584.50
#Mann=6,-1,0
  4512.7    0.07       0  4558.9   0.035       0  4566.1    0.07       0
  4722.8   0.035       0  5004.1   0.035       0  5008.4   0.035       0
Bank Sta=5004.1,5008.4
Exp/Cntr=0.3,0.1

Type RM Length L Ch R = 1,23532,347,347,347
BEGIN DESCRIPTION:
Mapping XS c593bbbc
END DESCRIPTION:
XS GIS Cut Line= 3
      1700819.23      7037283.85      1701046.01      7037886.05
      1701190.69      7038150.58
#Sta/Elev= 30
  4357.2 1584.62  4468.0 1580.58  4479.2 1579.64  4498.2 1579.49  4528.4 1578.12
  4533.8 1578.40  4543.3 1577.62  4558.7 1577.43  4613.7 1574.88  4637.2 1574.52
  4809.2 1569.18  4814.6 1569.49  4949.3 1567.95  4983.0 1565.22  4983.3 1564.72
  4987.1 1564.72  4987.3 1565.22  4992.1 1565.50  4999.1 1568.85  5004.6 1568.85
  5008.8 1571.59  5014.5 1572.36  5037.1 1574.57  5052.4 1574.56  5074.3 1577.37
  5090.4 1578.47  5112.2 1579.58  5199.5 1581.55  5215.6 1581.22  5302.2 1582.87
#Mann=4,-1,0
  4357.2    0.07       0  4637.2   0.035       0  4983.0   0.035       0
  4987.3   0.035       0
Bank Sta=4983,4987.3
Exp/Cntr=0.3,0.1

Type RM Length L Ch R = 1,23185,368,368,368
BEGIN DESCRIPTION:
Mapping XS 9bf2a96c
END DESCRIPTION:
XS GIS Cut Line= 3
      1700634.66      7037386.38      1700753.15      7037938.46
      1700880.39      7038338.35
#Sta/Elev= 30
  4439.5 1581.44  4533.2 1577.55  4543.4 1577.29  4553.7 1577.84  4574.1 1576.44
  4664.8 1573.74  4819.6 1569.29  4962.8 1567.88  4983.2 1567.14  4993.9 1565.78
  5001.4 1563.73  5026.1 1563.49  5026.4 1562.99  5030.2 1562.99  5030.5 1563.49
  5035.2 1563.57  5055.3 1568.90  5066.6 1570.48  5092.8 1572.08  5098.1 1573.15
  5125.0 1575.91  5194.7 1576.73  5221.7 1575.59  5227.0 1576.30  5234.5 1574.75
  5253.9 1573.20  5276.5 1574.33  5297.5 1576.49  5323.7 1576.91  5423.8 1580.57
#Mann=4,-1,0
  4439.5    0.07       0  4664.8   0.035       0  5026.1   0.035       0
  5030.5   0.035       0
Bank Sta=5026.1,5030.5
Exp/Cntr=0.3,0.1

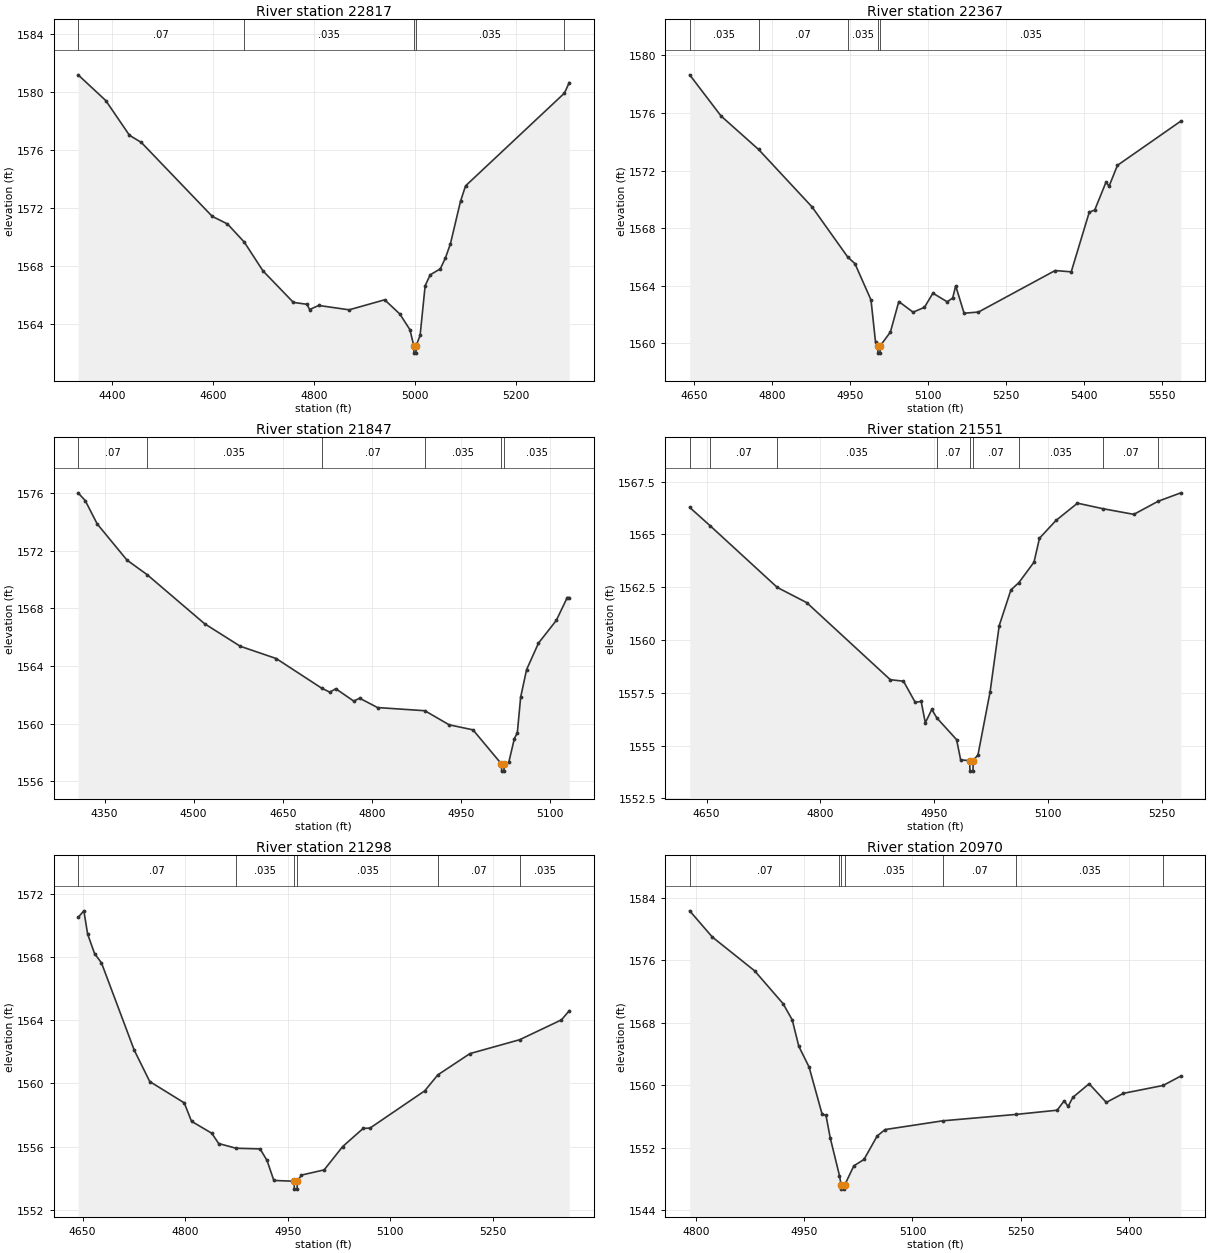
Type RM Length L Ch R = 1,22817,450,450,450
BEGIN DESCRIPTION:
Mapping XS 1f0b8d2e
END DESCRIPTION:
XS GIS Cut Line= 3
      1700488.83      7037373.35      1700431.53      7038042.62
      1700439.34      7038343.20
#Sta/Elev= 30
  4332.6 1581.16  4387.4 1579.39  4434.3 1577.00  4457.7 1576.51  4598.2 1571.42
  4628.3 1570.90  4661.6 1569.65  4698.6 1567.67  4758.8 1565.50  4785.9 1565.37
  4790.9 1565.01  4809.0 1565.29  4869.2 1564.99  4939.5 1565.68  4969.6 1564.70
  4989.6 1563.62  4997.2 1562.51  4997.6 1562.01  5001.4 1562.01  5001.7 1562.51
  5009.7 1563.23  5019.7 1566.65  5029.7 1567.40  5049.7 1567.81  5059.7 1568.55
  5069.7 1569.53  5089.7 1572.46  5099.7 1573.52  5295.4 1579.90  5305.0 1580.63
#Mann=5,-1,0
  4332.6    0.07       0  4661.6   0.035       0  4997.2   0.035       0
  5001.7   0.035       0  5295.4    0.07       0
Bank Sta=4997.2,5001.7
Exp/Cntr=0.3,0.1

Type RM Length L Ch R = 1,22367,520,520,520
BEGIN DESCRIPTION:
Mapping XS 4406166d
END DESCRIPTION:
XS GIS Cut Line= 3
      1700298.07      7037389.41      1700211.27      7037739.89
      1699933.82      7038253.59
#Sta/Elev= 30
  4641.7 1578.64  4702.1 1575.78  4774.3 1573.46  4877.2 1569.47  4945.7 1566.00
  4959.6 1565.54  4990.5 1563.02  4999.2 1560.10  5003.6 1559.83  5003.9 1559.33
  5007.8 1559.33  5008.1 1559.83  5027.8 1560.79  5044.0 1562.91  5071.5 1562.17
  5093.4 1562.51  5109.6 1563.49  5137.2 1562.89  5147.7 1563.16  5153.4 1564.00
  5169.6 1562.10  5197.2 1562.18  5344.7 1565.06  5375.7 1564.97  5410.4 1569.11
  5420.9 1569.26  5442.8 1571.21  5448.4 1570.90  5464.6 1572.36  5586.6 1575.43
#Mann=5,-1,0
  4641.7   0.035       0  4774.3    0.07       0  4945.7   0.035       0
  5003.6   0.035       0  5008.1   0.035       0
Bank Sta=5003.6,5008.1
Exp/Cntr=0.3,0.1

Type RM Length L Ch R = 1,21847,296,296,296
BEGIN DESCRIPTION:
Mapping XS c15d7b85
END DESCRIPTION:
XS GIS Cut Line= 3
      1699852.17      7037246.02      1699791.41      7037939.59
      1699787.07      7038069.79
#Sta/Elev= 30
  4305.5 1576.04  4317.5 1575.50  4337.6 1573.88  4387.8 1571.36  4421.7 1570.35
  4518.3 1566.94  4578.5 1565.37  4638.8 1564.52  4715.3 1562.46  4729.1 1562.18
  4739.1 1562.42  4769.3 1561.56  4779.3 1561.76  4809.4 1561.11  4889.0 1560.89
  4929.9 1559.91  4970.0 1559.56  5017.9 1557.19  5018.2 1556.69  5022.1 1556.69
  5022.4 1557.19  5030.2 1557.30  5039.6 1558.95  5044.6 1559.36  5050.2 1561.83
  5060.2 1563.75  5080.2 1565.59  5110.2 1567.17  5128.6 1568.76  5132.0 1568.76
#Mann=6,-1,0
  4305.5    0.07       0  4421.7   0.035       0  4715.3    0.07       0
  4889.0   0.035       0  5017.9   0.035       0  5022.4   0.035       0
Bank Sta=5017.9,5022.4
Exp/Cntr=0.3,0.1

Type RM Length L Ch R = 1,21551,253,253,253
BEGIN DESCRIPTION:
Mapping XS 9c9b299a
END DESCRIPTION:
XS GIS Cut Line= 3
      1699734.03      7037425.93      1699582.97      7037768.85
      1699449.64      7038006.94
#Sta/Elev= 30
  4627.7 1566.28  4655.0 1565.40  4743.2 1562.49  4782.0 1561.77  4892.2 1558.12
  4909.6 1558.05  4925.0 1557.05  4932.9 1557.09  4938.4 1556.08  4946.9 1556.71
  4953.6 1556.31  4979.6 1555.28  4985.0 1554.32  4996.9 1554.29  4997.2 1553.79
  5001.2 1553.79  5001.5 1554.29  5007.8 1554.56  5023.8 1557.55  5035.8 1560.68
  5051.2 1562.37  5061.8 1562.72  5081.7 1563.69  5088.9 1564.82  5110.6 1565.66
  5139.0 1566.48  5172.3 1566.22  5213.3 1565.95  5245.3 1566.57  5275.3 1566.97
#Mann=9,-1,0
  4627.7   0.035       0  4655.0    0.07       0  4743.2   0.035       0
  4953.6    0.07       0  4996.9    0.07       0  5001.5    0.07       0
  5061.8   0.035       0  5172.3    0.07       0  5245.3   0.035       0
Bank Sta=4996.9,5001.5
Exp/Cntr=0.3,0.1

Type RM Length L Ch R = 1,21298,328,328,328
BEGIN DESCRIPTION:
Mapping XS f8f46025
END DESCRIPTION:
XS GIS Cut Line= 3
      1699451.03      7037234.10      1699404.15      7037590.90
      1699397.21      7037949.37
#Sta/Elev= 30
  4643.5 1570.52  4651.9 1570.94  4657.5 1569.46  4667.6 1568.23  4677.7 1567.64
  4725.6 1562.11  4748.3 1560.12  4798.7 1558.77  4809.4 1557.60  4839.1 1556.84
  4849.1 1556.19  4874.6 1555.89  4909.7 1555.85  4919.8 1555.12  4929.8 1553.85
  4959.5 1553.80  4959.8 1553.30  4963.8 1553.30  4964.1 1553.80  4970.2 1554.19
  5003.4 1554.52  5030.5 1556.00  5060.5 1557.15  5070.5 1557.17  5150.5 1559.53
  5169.6 1560.54  5216.6 1561.89  5289.3 1562.77  5350.5 1564.03  5361.9 1564.61
#Mann=6,-1,0
  4643.5    0.07       0  4874.6   0.035       0  4959.5   0.035       0
  4964.1   0.035       0  5169.6    0.07       0  5289.3   0.035       0
Bank Sta=4959.5,4964.1
Exp/Cntr=0.3,0.1

Type RM Length L Ch R = 1,20970,187,187,187
BEGIN DESCRIPTION:
Mapping XS 616f3744
END DESCRIPTION:
XS GIS Cut Line= 3
      1699074.49      7037199.36      1699158.71      7037392.11
      1699341.00      7037826.14
#Sta/Elev= 30
  4791.1 1582.35  4822.4 1579.00  4881.1 1574.67  4920.6 1570.46  4933.3 1568.38
  4942.4 1565.00  4956.7 1562.33  4974.7 1556.31  4980.1 1556.15  4986.0 1553.26
  4998.8 1548.43  5001.2 1547.20  5001.6 1546.70  5005.6 1546.70  5005.9 1547.20
  5018.7 1549.68  5032.8 1550.50  5051.1 1553.51  5062.1 1554.33  5141.9 1555.45
  5243.6 1556.27  5300.7 1556.81  5310.4 1558.02  5315.8 1557.29  5322.4 1558.45
  5345.0 1560.20  5368.8 1557.81  5392.5 1558.97  5447.6 1559.98  5472.2 1561.19
#Mann=7,-1,0
  4791.1    0.07       0  4998.8   0.035       0  5001.2   0.035       0
  5005.9   0.035       0  5141.9    0.07       0  5243.6   0.035       0
  5447.6    0.07       0
Bank Sta=5001.2,5005.9
Exp/Cntr=0.3,0.1

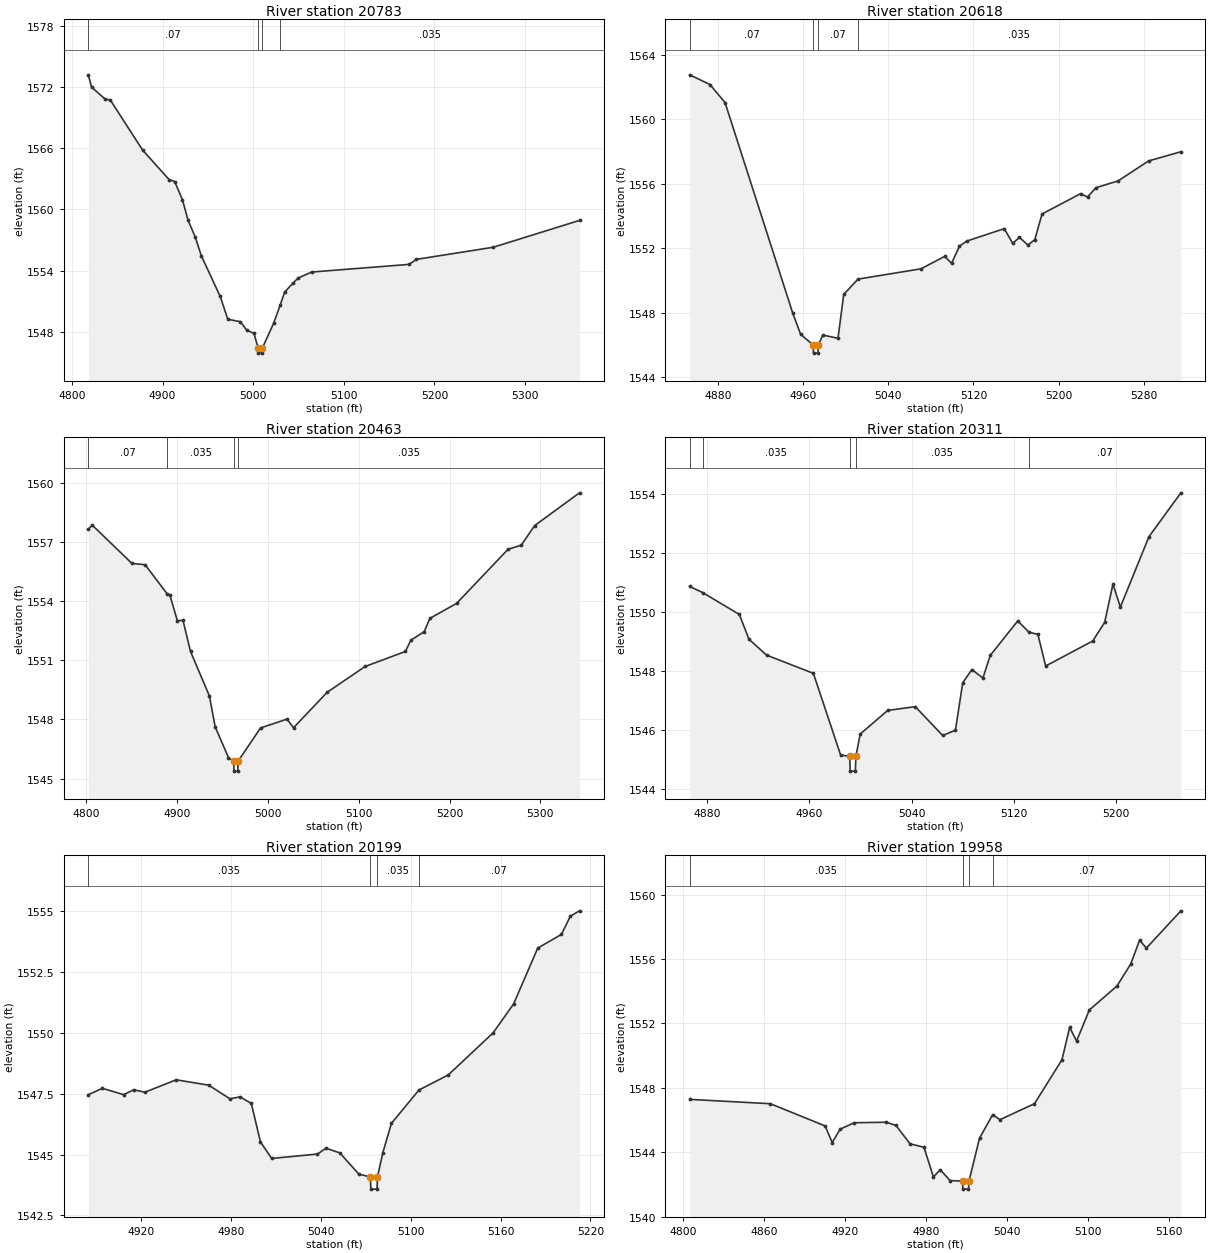
Type RM Length L Ch R = 1,20783,165,165,165
BEGIN DESCRIPTION:
Mapping XS fe1255fa
END DESCRIPTION:
XS GIS Cut Line= 3
      1698925.97      7037362.84      1699034.32      7037510.08
      1699237.07      7037806.57
#Sta/Elev= 30
  4818.1 1573.20  4821.6 1572.01  4836.2 1570.85  4842.5 1570.71  4878.0 1565.82
  4907.2 1562.93  4913.4 1562.74  4921.9 1560.96  4928.1 1558.96  4936.2 1557.26
  4942.7 1555.48  4963.6 1551.48  4972.0 1549.24  4985.9 1549.00  4992.9 1548.16
  5000.9 1547.86  5005.4 1546.42  5005.7 1545.92  5009.7 1545.92  5010.1 1546.42
  5022.6 1548.85  5030.0 1550.68  5034.7 1551.90  5043.6 1552.75  5049.7 1553.29
  5064.6 1553.87  5172.2 1554.62  5180.1 1555.11  5265.0 1556.30  5360.1 1558.93
#Mann=4,-1,0
  4818.1    0.07       0  5005.4    0.07       0  5010.1    0.07       0
  5030.0   0.035       0
Bank Sta=5005.4,5010.1
Exp/Cntr=0.3,0.1

Type RM Length L Ch R = 1,20618,155,155,155
BEGIN DESCRIPTION:
Mapping XS fe519627
END DESCRIPTION:
XS GIS Cut Line= 3
      1698819.27      7037516.69      1698917.22      7037625.06
      1699117.23      7037868.83
#Sta/Elev= 30
  4853.4 1562.77  4872.4 1562.17  4886.6 1561.05  4950.1 1548.01  4957.6 1546.68
  4969.4 1546.01  4969.7 1545.51  4973.8 1545.51  4974.2 1546.01  4978.5 1546.63
  4992.7 1546.43  4998.1 1549.15  5011.5 1550.10  5070.7 1550.74  5092.9 1551.51
  5099.4 1551.08  5106.8 1552.14  5113.7 1552.46  5148.9 1553.23  5156.8 1552.32
  5163.2 1552.69  5171.1 1552.21  5177.6 1552.55  5184.4 1554.14  5220.6 1555.40
  5227.1 1555.19  5235.0 1555.77  5255.8 1556.19  5284.5 1557.43  5314.8 1558.00
#Mann=4,-1,0
  4853.4    0.07       0  4969.4    0.07       0  4974.2    0.07       0
  5011.5   0.035       0
Bank Sta=4969.4,4974.2
Exp/Cntr=0.3,0.1

Type RM Length L Ch R = 1,20463,152,152,152
BEGIN DESCRIPTION:
Mapping XS d463e7ad
END DESCRIPTION:
XS GIS Cut Line= 3
      1698688.73      7037577.82      1698808.88      7037736.17
      1699008.77      7038013.10
#Sta/Elev= 30
  4802.7 1557.66  4807.0 1557.86  4850.6 1555.92  4865.2 1555.85  4889.6 1554.36
  4892.3 1554.33  4900.6 1553.01  4906.8 1553.03  4915.1 1551.45  4935.9 1549.19
  4942.2 1547.63  4956.8 1546.07  4962.6 1545.88  4963.0 1545.38  4967.1 1545.38
  4967.4 1545.88  4992.1 1547.57  5021.3 1548.02  5028.4 1547.58  5065.4 1549.38
  5107.2 1550.69  5151.4 1551.45  5157.5 1552.02  5172.2 1552.46  5178.4 1553.13
  5207.8 1553.89  5264.3 1556.63  5279.0 1556.85  5293.7 1557.84  5343.0 1559.50
#Mann=4,-1,0
  4802.7    0.07       0  4889.6   0.035       0  4962.6   0.035       0
  4967.4   0.035       0
Bank Sta=4962.6,4967.4
Exp/Cntr=0.3,0.1

Type RM Length L Ch R = 1,20311,112,112,112
BEGIN DESCRIPTION:
Mapping XS b07ca32b
END DESCRIPTION:
XS GIS Cut Line= 3
      1698630.52      7037728.44      1698700.83      7037843.03
      1698826.33      7038059.66
#Sta/Elev= 30
  4866.2 1550.86  4876.5 1550.65  4905.1 1549.91  4912.6 1549.07  4926.4 1548.53
  4963.1 1547.91  4984.4 1545.14  4991.6 1545.09  4991.9 1544.59  4996.0 1544.59
  4996.4 1545.09  4999.8 1545.85  5021.3 1546.65  5042.9 1546.78  5064.4 1545.80
  5074.4 1545.98  5080.1 1547.59  5087.3 1548.04  5095.9 1547.75  5101.7 1548.52
  5123.2 1549.69  5132.0 1549.31  5139.0 1549.23  5145.1 1548.16  5182.0 1549.01
  5191.3 1549.64  5197.8 1550.94  5203.6 1550.16  5226.0 1552.55  5251.0 1554.04
#Mann=5,-1,0
  4866.2    0.07       0  4876.5   0.035       0  4991.6   0.035       0
  4996.4   0.035       0  5132.0    0.07       0
Bank Sta=4991.6,4996.4
Exp/Cntr=0.3,0.1

Type RM Length L Ch R = 1,20199,241,241,241
BEGIN DESCRIPTION:
Mapping XS 3162e407
END DESCRIPTION:
XS GIS Cut Line= 3
      1698544.03      7037835.70      1698621.14      7037922.19
      1698722.71      7038108.66
#Sta/Elev= 30
  4884.5 1547.46  4893.9 1547.72  4908.1 1547.46  4914.8 1547.66  4922.3 1547.56
  4943.2 1548.07  4964.9 1547.85  4979.1 1547.29  4985.8 1547.37  4993.4 1547.10
  4999.5 1545.52  5007.0 1544.84  5037.6 1545.02  5043.3 1545.26  5052.5 1545.07
  5065.2 1544.20  5072.9 1544.08  5073.3 1543.58  5077.4 1543.58  5077.7 1544.08
  5081.3 1545.08  5087.0 1546.28  5105.4 1547.65  5125.0 1548.27  5155.0 1550.00
  5168.7 1551.19  5184.8 1553.48  5200.6 1554.04  5206.6 1554.79  5212.7 1555.01
#Mann=4,-1,0
  4884.5   0.035       0  5072.9   0.035       0  5077.7   0.035       0
  5105.4    0.07       0
Bank Sta=5072.9,5077.7
Exp/Cntr=0.3,0.1

Type RM Length L Ch R = 1,19958,142,142,142
BEGIN DESCRIPTION:
Mapping XS 47f46f69
END DESCRIPTION:
XS GIS Cut Line= 3
      1698557.05      7037900.24      1698506.28      7038090.31
      1698474.47      7038254.52
#Sta/Elev= 30
  4804.7 1547.29  4864.5 1547.02  4905.1 1545.64  4910.3 1544.61  4916.2 1545.44
  4926.6 1545.84  4950.4 1545.87  4957.6 1545.67  4968.0 1544.53  4978.3 1544.32
  4985.3 1542.48  4990.4 1542.92  4997.7 1542.25  5006.9 1542.22  5007.2 1541.72
  5011.3 1541.72  5011.7 1542.22  5019.5 1544.88  5029.2 1546.34  5034.6 1546.03
  5060.2 1547.02  5080.6 1549.75  5086.3 1551.76  5091.4 1550.91  5100.9 1552.84
  5121.3 1554.32  5131.5 1555.68  5138.1 1557.16  5143.2 1556.68  5168.7 1558.99
#Mann=4,-1,0
  4804.7   0.035       0  5006.9   0.035       0  5011.7   0.035       0
  5029.2    0.07       0
Bank Sta=5006.9,5011.7
Exp/Cntr=0.3,0.1

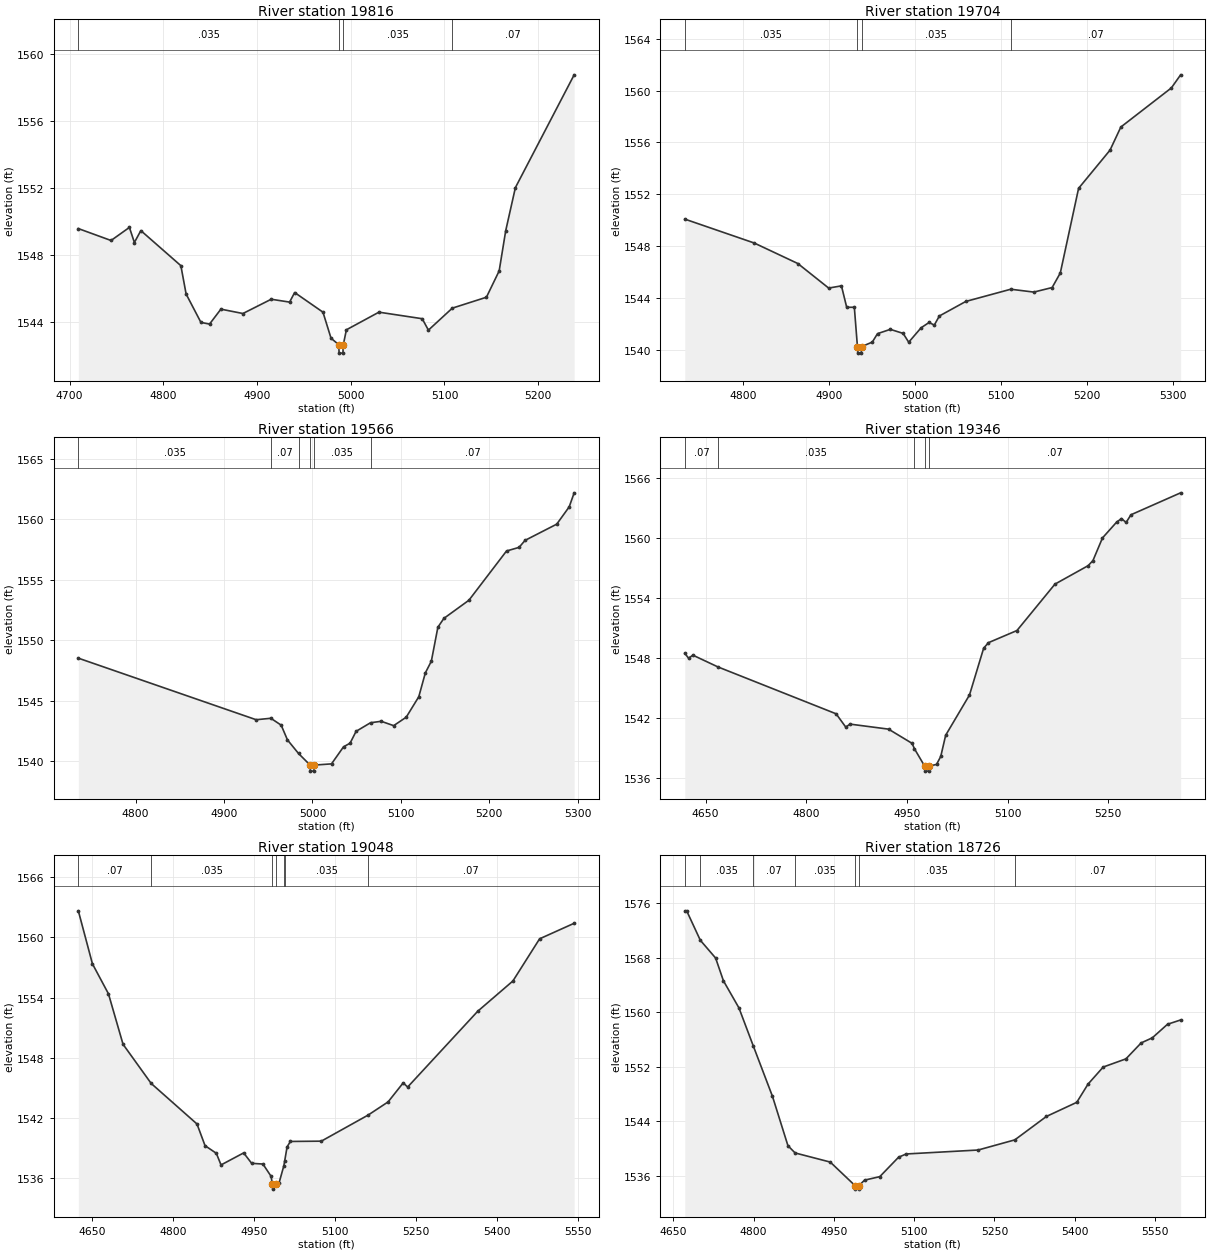
Type RM Length L Ch R = 1,19816,112,112,112
BEGIN DESCRIPTION:
Mapping XS a3171e18
END DESCRIPTION:
XS GIS Cut Line= 3
      1698279.55      7037765.55      1698381.98      7038039.00
      1698440.08      7038268.76
#Sta/Elev= 30
  4709.4 1549.59  4744.3 1548.88  4763.9 1549.66  4769.2 1548.76  4776.1 1549.47
  4818.8 1547.38  4824.4 1545.69  4840.2 1544.00  4849.4 1543.90  4861.5 1544.79
  4885.0 1544.53  4915.2 1545.38  4934.8 1545.21  4940.2 1545.78  4970.4 1544.61
  4979.0 1543.06  4987.3 1542.67  4987.6 1542.17  4991.7 1542.17  4992.1 1542.67
  4995.4 1543.56  5030.1 1544.61  5076.3 1544.22  5082.9 1543.54  5108.4 1544.85
  5144.8 1545.50  5158.4 1547.07  5165.4 1549.47  5175.7 1552.03  5238.4 1558.75
#Mann=4,-1,0
  4709.4   0.035       0  4987.3   0.035       0  4992.1   0.035       0
  5108.4    0.07       0
Bank Sta=4987.3,4992.1
Exp/Cntr=0.3,0.1

Type RM Length L Ch R = 1,19704,138,138,138
BEGIN DESCRIPTION:
Mapping XS 6d302a29
END DESCRIPTION:
XS GIS Cut Line= 3
      1698126.76      7037842.80      1698278.69      7038065.04
      1698440.49      7038327.22
#Sta/Elev= 30
  4731.8 1550.10  4812.6 1548.26  4863.4 1546.68  4899.3 1544.79  4914.2 1544.96
  4920.3 1543.31  4929.2 1543.31  4932.8 1540.28  4933.2 1539.78  4937.3 1539.78
  4937.6 1540.28  4950.1 1540.63  4956.2 1541.28  4971.1 1541.61  4986.0 1541.30
  4992.5 1540.62  5006.9 1541.73  5016.2 1542.14  5022.3 1541.94  5028.2 1542.64
  5059.0 1543.76  5111.3 1544.70  5138.2 1544.48  5159.5 1544.83  5169.0 1545.95
  5190.3 1552.47  5226.9 1555.41  5239.5 1557.19  5298.3 1560.20  5309.1 1561.21
#Mann=4,-1,0
  4731.8   0.035       0  4932.8   0.035       0  4937.6   0.035       0
  5111.3    0.07       0
Bank Sta=4932.8,4937.6
Exp/Cntr=0.3,0.1

Type RM Length L Ch R = 1,19566,220,220,220
BEGIN DESCRIPTION:
Mapping XS fcc061c5
END DESCRIPTION:
XS GIS Cut Line= 3
      1697990.94      7037977.58      1698181.06      7038162.50
      1698381.19      7038379.88
#Sta/Elev= 30
  4735.2 1548.52  4936.3 1543.43  4952.9 1543.55  4964.6 1542.98  4971.7 1541.76
  4984.2 1540.64  4997.3 1539.68  4997.6 1539.18  5001.7 1539.18  5002.1 1539.68
  5021.5 1539.78  5035.1 1541.19  5042.5 1541.49  5049.3 1542.47  5065.6 1543.18
  5077.7 1543.30  5091.8 1542.94  5106.0 1543.64  5120.2 1545.33  5127.6 1547.30
  5134.4 1548.27  5141.8 1551.08  5148.6 1551.81  5176.9 1553.31  5219.4 1557.38
  5233.6 1557.68  5240.4 1558.26  5276.2 1559.60  5290.3 1561.03  5295.9 1562.19
#Mann=6,-1,0
  4735.2   0.035       0  4952.9    0.07       0  4984.2   0.035       0
  4997.3   0.035       0  5002.1   0.035       0  5065.6    0.07       0
Bank Sta=4997.3,5002.1
Exp/Cntr=0.3,0.1

Type RM Length L Ch R = 1,19346,298,298,298
BEGIN DESCRIPTION:
Mapping XS ea4adc9d
END DESCRIPTION:
XS GIS Cut Line= 3
      1697805.22      7038040.14      1698050.85      7038332.64
      1698307.77      7038580.01
#Sta/Elev= 30
  4619.1 1548.47  4624.7 1547.98  4631.2 1548.28  4668.4 1547.11  4844.5 1542.43
  4858.8 1541.11  4865.4 1541.40  4922.6 1540.90  4957.7 1539.48  4961.2 1538.94
  4976.4 1537.21  4976.9 1536.71  4982.6 1536.71  4983.1 1537.21  4994.1 1537.38
  5000.4 1538.18  5007.7 1540.29  5043.2 1544.31  5064.3 1548.98  5071.5 1549.53
  5113.9 1550.74  5170.5 1555.37  5219.9 1557.21  5227.1 1557.72  5241.3 1559.98
  5262.4 1561.56  5269.6 1561.91  5276.5 1561.52  5283.7 1562.29  5357.7 1564.48
#Mann=5,-1,0
  4619.1    0.07       0  4668.4   0.035       0  4961.2    0.07       0
  4976.4    0.07       0  4983.1    0.07       0
Bank Sta=4976.4,4983.1
Exp/Cntr=0.3,0.1

Type RM Length L Ch R = 1,19048,322,322,322
BEGIN DESCRIPTION:
Mapping XS ca238bf6
END DESCRIPTION:
XS GIS Cut Line= 3
      1697555.31      7038081.15      1697772.33      7038391.49
      1698067.47      7038842.87
#Sta/Elev= 30
  4625.2 1562.65  4651.3 1557.37  4681.0 1554.38  4708.0 1549.35  4760.1 1545.45
  4844.9 1541.41  4859.8 1539.25  4880.7 1538.49  4889.4 1537.33  4931.3 1538.53
  4946.1 1537.49  4967.0 1537.42  4981.9 1536.21  4984.6 1535.42  4985.1 1534.92
  4991.4 1535.42  4996.7 1535.51  5005.8 1537.27  5007.4 1537.77  5011.7 1539.13
  5017.8 1539.67  5075.1 1539.70  5161.8 1542.30  5198.7 1543.61  5226.7 1545.51
  5234.9 1545.09  5364.6 1552.64  5429.8 1555.66  5479.2 1559.86  5543.2 1561.41
#Mann=7,-1,0
  4625.2    0.07       0  4760.1   0.035       0  4984.6   0.035       0
  4991.4   0.035       0  5005.8    0.07       0  5007.4   0.035       0
  5161.8    0.07       0
Bank Sta=4984.6,4991.4
Exp/Cntr=0.3,0.1

Type RM Length L Ch R = 1,18726,364,364,364
BEGIN DESCRIPTION:
Mapping XS ad5bd5a4
END DESCRIPTION:
XS GIS Cut Line= 3
      1697274.32      7038258.05      1697537.96      7038457.68
      1697978.48      7038859.14
#Sta/Elev= 30
  4671.4 1574.92  4674.9 1574.92  4700.4 1570.60  4729.0 1567.99  4743.6 1564.65
  4772.6 1560.67  4799.3 1555.11  4835.3 1547.68  4864.2 1540.44  4877.6 1539.38
  4943.3 1538.04  4989.8 1534.57  4990.3 1534.07  4996.1 1534.07  4996.6 1534.57
  5007.4 1535.39  5035.8 1535.90  5070.9 1538.75  5085.1 1539.23  5219.6 1539.81
  5288.2 1541.30  5347.3 1544.74  5404.0 1546.81  5425.0 1549.48  5453.4 1551.99
  5495.9 1553.19  5524.3 1555.53  5545.2 1556.28  5573.6 1558.27  5598.1 1558.90
#Mann=7,-1,0
  4671.4    0.07       0  4700.4   0.035       0  4799.3    0.07       0
  4877.6   0.035       0  4989.8   0.035       0  4996.6   0.035       0
  5288.2    0.07       0
Bank Sta=4989.8,4996.6
Exp/Cntr=0.3,0.1

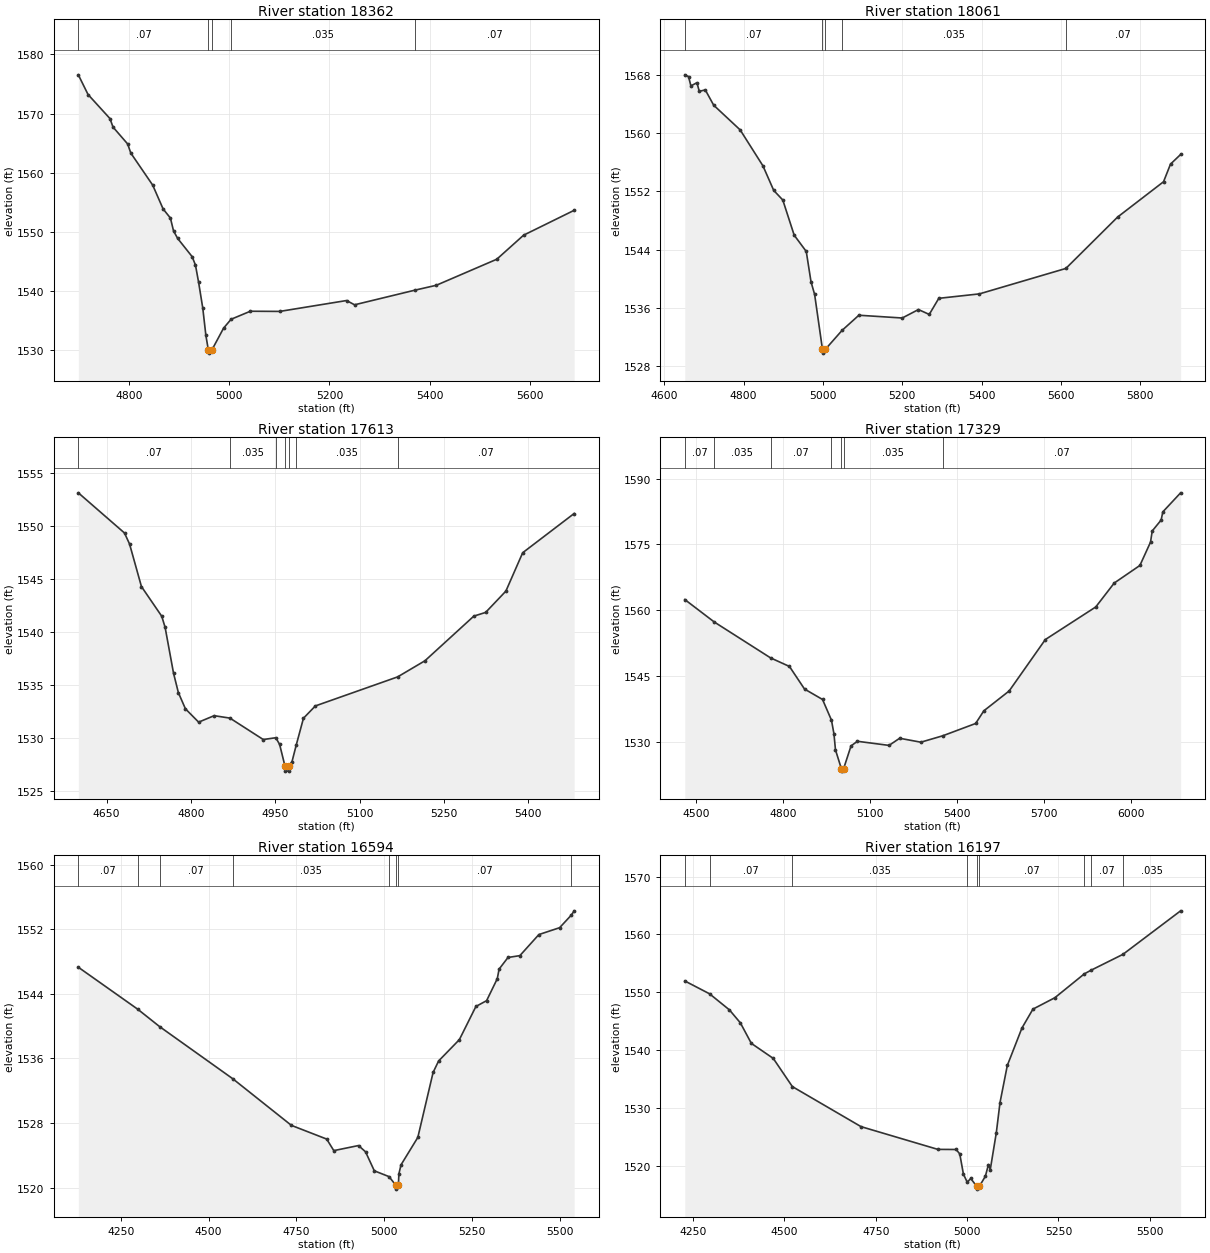
Type RM Length L Ch R = 1,18362,301,301,301
BEGIN DESCRIPTION:
Mapping XS 3f98f272
END DESCRIPTION:
XS GIS Cut Line= 3
      1697012.49      7038452.87      1697255.57      7038634.09
      1697874.04      7038935.73
#Sta/Elev= 30
  4697.9 1576.55  4717.3 1573.22  4761.1 1569.15  4767.3 1567.70  4796.5 1564.85
  4802.8 1563.31  4846.6 1557.88  4867.4 1553.85  4882.0 1552.31  4888.3 1550.12
  4896.6 1548.85  4925.5 1545.77  4932.1 1544.34  4938.3 1541.47  4946.7 1537.07
  4952.9 1532.45  4957.9 1529.95  4958.4 1529.45  4964.7 1529.95  4988.3 1533.68
  5003.3 1535.18  5041.8 1536.54  5100.6 1536.51  5234.1 1538.35  5250.2 1537.63
  5370.5 1540.10  5413.5 1540.93  5534.5 1545.34  5588.1 1549.41  5689.2 1553.62
#Mann=5,-1,0
  4697.9    0.07       0  4957.9    0.07       0  4964.7    0.07       0
  5003.3   0.035       0  5370.5    0.07       0
Bank Sta=4957.9,4964.7
Exp/Cntr=0.3,0.1

Type RM Length L Ch R = 1,18061,448,448,448
BEGIN DESCRIPTION:
Mapping XS 6b562b7d
END DESCRIPTION:
XS GIS Cut Line= 3
      1696746.66      7038614.98      1697042.26      7038803.80
      1697919.87      7039003.02
#Sta/Elev= 30
  4651.5 1568.00  4660.9 1567.76  4666.9 1566.48  4682.1 1566.92  4688.0 1565.74
  4703.2 1565.93  4724.4 1563.83  4791.2 1560.44  4848.7 1555.50  4875.8 1552.14
  4898.7 1550.82  4927.4 1546.00  4957.9 1543.76  4969.9 1539.59  4979.0 1537.86
  4998.8 1530.31  4999.3 1529.81  5005.7 1530.31  5048.0 1532.92  5090.6 1535.01
  5199.9 1534.63  5240.9 1535.79  5268.1 1535.12  5292.2 1537.33  5394.7 1537.94
  5612.7 1541.43  5743.4 1548.49  5859.1 1553.33  5876.7 1555.75  5902.2 1557.07
#Mann=5,-1,0
  4651.5    0.07       0  4998.8    0.07       0  5005.7    0.07       0
  5048.0   0.035       0  5612.7    0.07       0
Bank Sta=4998.8,5005.7
Exp/Cntr=0.3,0.1

Type RM Length L Ch R = 1,17613,284,284,284
BEGIN DESCRIPTION:
Mapping XS 23921673
END DESCRIPTION:
XS GIS Cut Line= 3
      1696727.96      7038849.65      1696949.30      7039183.83
      1697347.71      7039452.91
#Sta/Elev= 30
  4599.8 1553.10  4681.9 1549.31  4690.9 1548.27  4712.0 1544.26  4748.1 1541.46
  4754.1 1540.41  4769.1 1536.08  4777.7 1534.25  4790.2 1532.73  4813.7 1531.47
  4841.3 1532.08  4869.4 1531.85  4928.6 1529.83  4950.9 1530.00  4957.7 1529.37
  4967.1 1527.35  4967.6 1526.85  4973.8 1526.85  4974.3 1527.35  4979.7 1527.74
  4987.4 1529.34  5000.1 1531.84  5021.3 1533.00  5167.6 1535.74  5216.1 1537.26
  5303.0 1541.47  5324.0 1541.82  5360.0 1543.83  5389.9 1547.45  5481.4 1551.15
#Mann=7,-1,0
  4599.8    0.07       0  4869.4   0.035       0  4950.9    0.07       0
  4967.1   0.035       0  4974.3    0.07       0  4987.4   0.035       0
  5167.6    0.07       0
Bank Sta=4967.1,4974.3
Exp/Cntr=0.3,0.1

Type RM Length L Ch R = 1,17329,735,735,735
BEGIN DESCRIPTION:
Mapping XS 949b0dc5
END DESCRIPTION:
XS GIS Cut Line= 3
      1696521.97      7038670.16      1696667.37      7039195.35
      1697283.08      7040183.95
#Sta/Elev= 30
  4460.6 1562.41  4561.9 1557.30  4756.3 1549.10  4821.5 1547.14  4873.4 1541.99
  4935.5 1539.61  4966.3 1534.89  4974.9 1531.76  4980.1 1528.12  5000.7 1523.76
  5001.2 1523.26  5007.9 1523.76  5033.8 1529.02  5055.8 1530.07  5164.8 1529.13
  5201.4 1530.76  5274.5 1529.86  5350.3 1531.33  5463.4 1534.13  5491.7 1537.02
  5579.0 1541.55  5703.7 1553.28  5877.6 1560.72  5941.3 1566.18  6029.8 1570.19
  6066.4 1575.51  6072.3 1578.06  6103.0 1580.55  6108.9 1582.42  6170.2 1586.76
#Mann=7,-1,0
  4460.6    0.07       0  4561.9   0.035       0  4756.3    0.07       0
  4966.3   0.035       0  5000.7   0.035       0  5007.9   0.035       0
  5350.3    0.07       0
Bank Sta=5000.7,5007.9
Exp/Cntr=0.3,0.1

Type RM Length L Ch R = 1,16594,397,397,397
BEGIN DESCRIPTION:
Mapping XS 2a66a611
END DESCRIPTION:
XS GIS Cut Line= 3
      1696276.37      7038954.84      1696373.59      7039824.64
      1696467.25      7040353.60
#Sta/Elev= 30
  4128.8 1547.29  4298.0 1542.09  4360.2 1539.94  4568.9 1533.47  4735.7 1527.70
  4836.3 1526.00  4856.5 1524.57  4926.9 1525.20  4947.0 1524.42  4971.9 1522.07
  5013.8 1521.35  5032.9 1520.30  5033.4 1519.80  5040.6 1520.30  5041.9 1521.68
  5048.0 1522.81  5095.9 1526.21  5139.4 1534.26  5155.1 1535.68  5214.2 1538.32
  5261.3 1542.43  5291.8 1543.15  5322.2 1545.87  5327.4 1547.06  5352.7 1548.50
  5386.6 1548.73  5440.7 1551.34  5499.8 1552.19  5533.3 1553.76  5541.2 1554.28
#Mann=8,-1,0
  4128.8    0.07       0  4298.0   0.035       0  4360.2    0.07       0
  4568.9   0.035       0  5013.8    0.07       0  5032.9   0.035       0
  5040.6    0.07       0  5533.3   0.035       0
Bank Sta=5032.9,5040.6
Exp/Cntr=0.3,0.1

Type RM Length L Ch R = 1,16197,485,485,485
BEGIN DESCRIPTION:
Mapping XS da45df35
END DESCRIPTION:
XS GIS Cut Line= 3
      1695995.12      7039065.99      1696017.69      7039840.26
      1696040.26      7040421.83
#Sta/Elev= 30
  4227.7 1551.97  4295.4 1549.75  4349.8 1546.97  4379.8 1544.72  4409.8 1541.18
  4469.8 1538.58  4522.0 1533.71  4709.9 1526.79  4920.0 1522.86  4970.0 1522.84
  4980.0 1522.08  4990.0 1518.59  5000.4 1517.19  5010.0 1517.83  5026.2 1516.49
  5026.7 1515.99  5033.9 1516.49  5050.1 1518.22  5058.5 1520.23  5063.5 1519.37
  5080.1 1525.77  5090.1 1530.94  5110.1 1537.36  5150.1 1543.83  5180.2 1547.10
  5240.2 1549.07  5320.9 1553.20  5338.8 1553.81  5426.3 1556.56  5584.3 1564.09
#Mann=9,-1,0
  4227.7   0.035       0  4295.4    0.07       0  4522.0   0.035       0
  5000.4    0.07       0  5026.2   0.035       0  5033.9    0.07       0
  5320.9   0.035       0  5338.8    0.07       0  5426.3   0.035       0
Bank Sta=5026.2,5033.9
Exp/Cntr=0.3,0.1