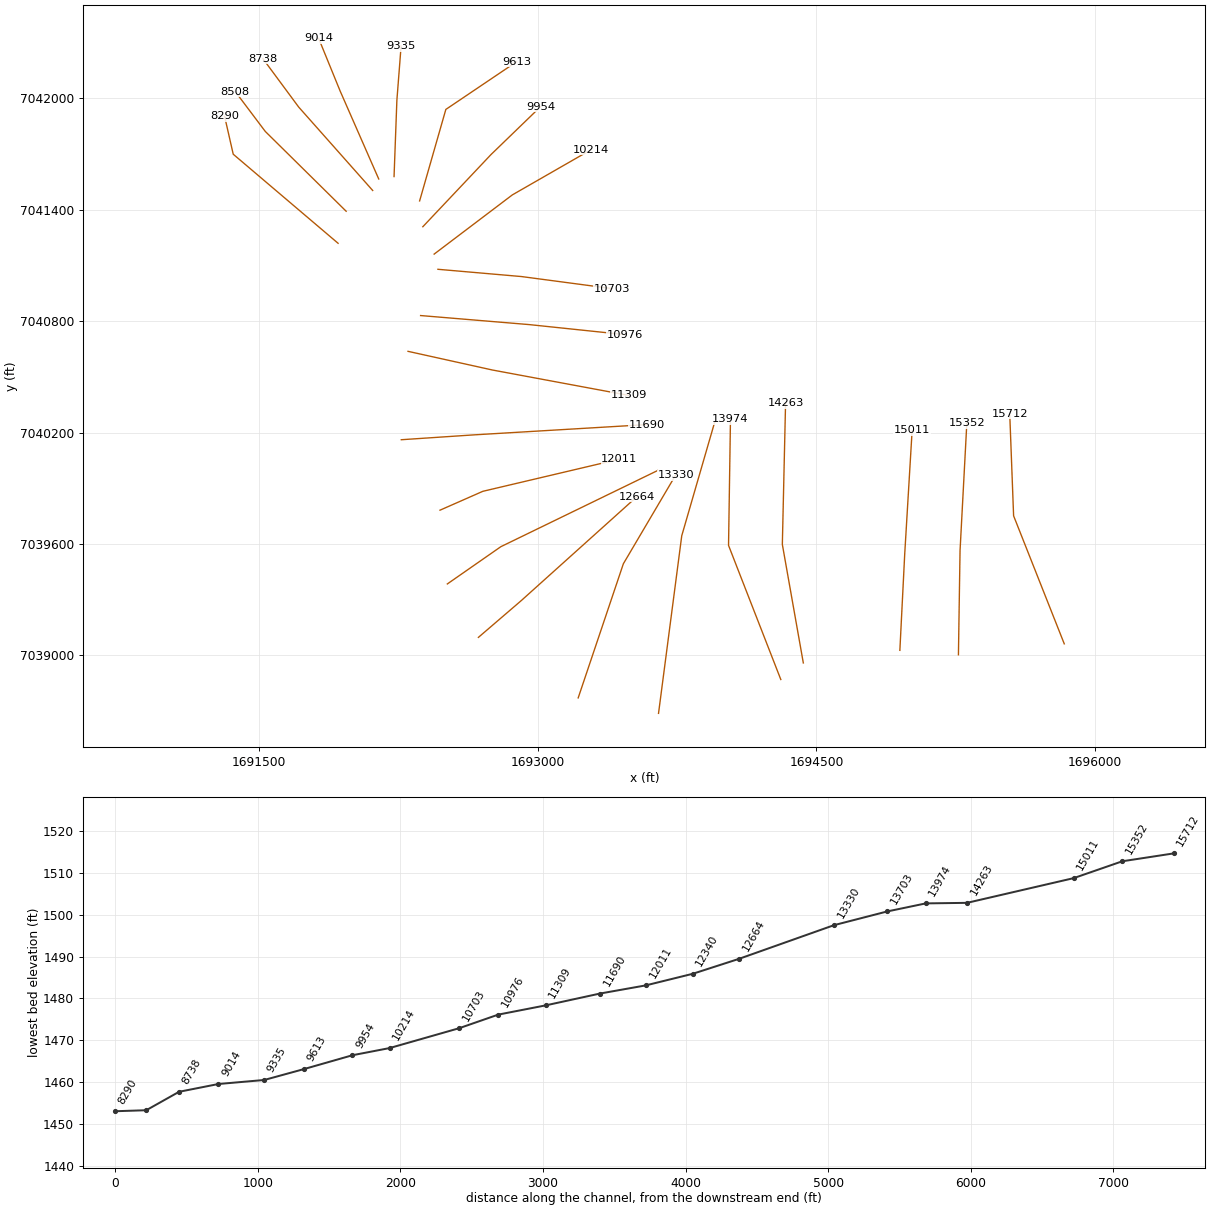
HEC-RAS study Chimney Creek 1192.prj: Chimney Creek 1192 Base Level Engineering

--- Chimney Creek 1192.g01 (geometry) --- (continued)

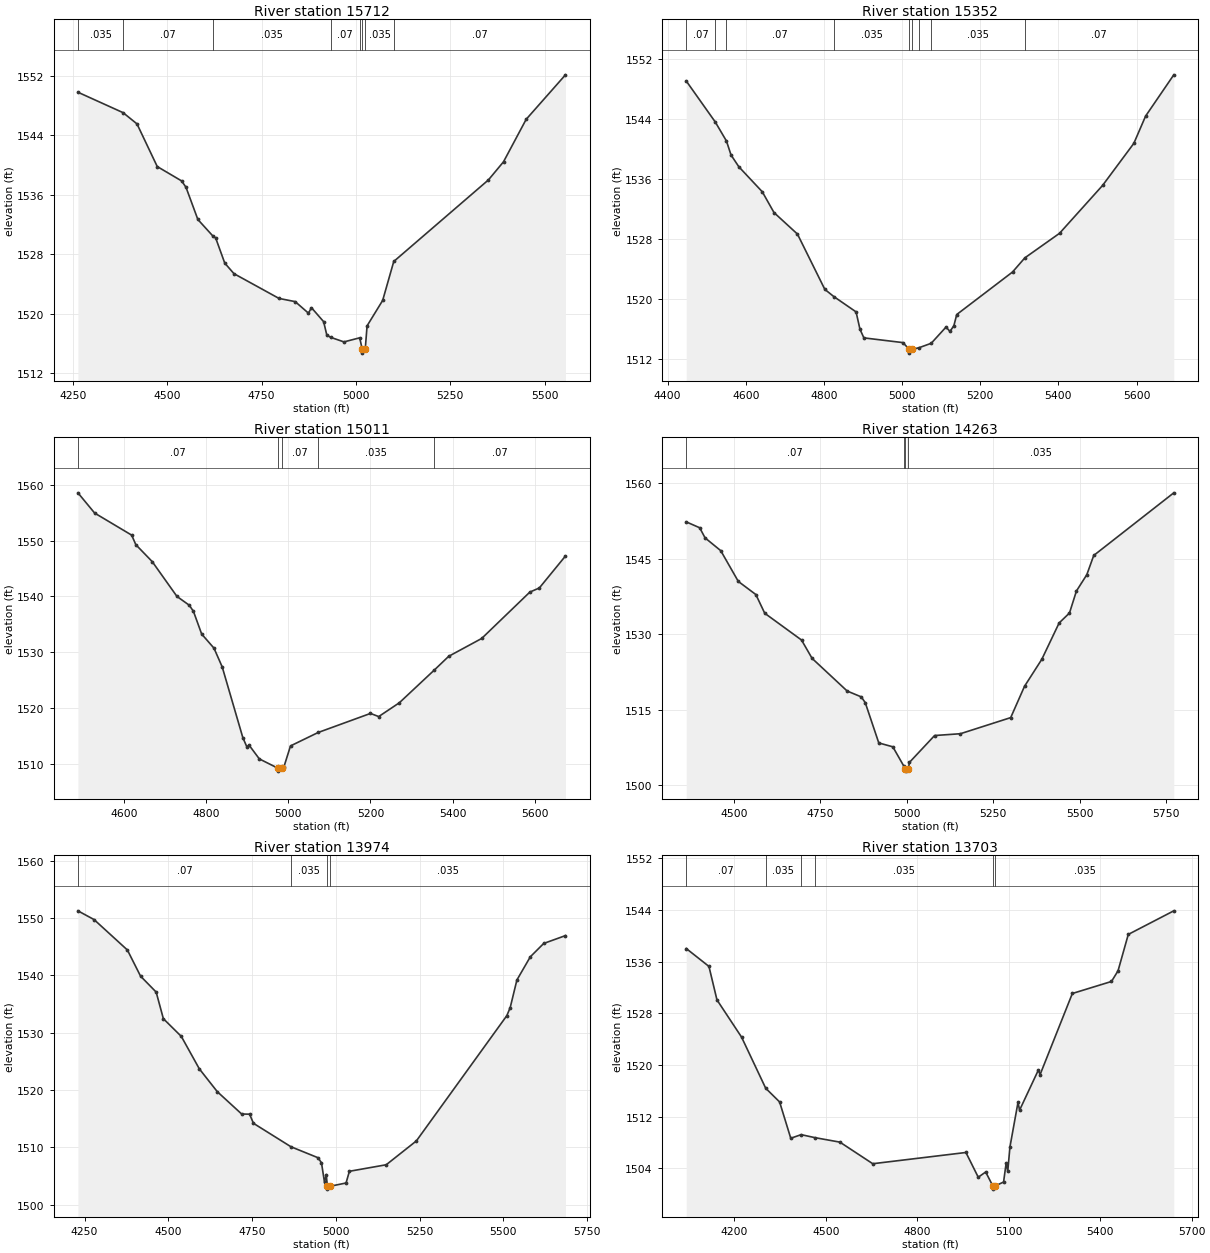
Type RM Length L Ch R = 1,15712,360,360,360
BEGIN DESCRIPTION:
Mapping XS a94f7401
END DESCRIPTION:
XS GIS Cut Line= 3
      1695833.65      7039062.51      1695561.09      7039751.72
      1695540.26      7040302.08
#Sta/Elev= 30
  4263.1 1549.77  4382.8 1547.02  4419.6 1545.51  4473.3 1539.77  4537.8 1537.84
  4549.5 1536.98  4580.9 1532.65  4621.7 1530.37  4627.9 1530.19  4652.2 1526.78
  4676.6 1525.36  4795.9 1522.03  4838.8 1521.60  4873.9 1520.05  4882.0 1520.78
  4914.2 1518.90  4922.6 1517.10  4932.5 1516.80  4968.0 1516.18  5009.7 1516.73
  5016.6 1515.17  5017.1 1514.67  5024.4 1515.17  5029.3 1518.34  5070.6 1521.76
  5100.0 1527.00  5350.8 1537.97  5390.8 1540.41  5450.8 1546.12  5555.0 1552.11
#Mann=8,-1,0
  4263.1   0.035       0  4382.8    0.07       0  4621.7   0.035       0
  4932.5    0.07       0  5009.7   0.035       0  5016.6    0.07       0
  5024.4   0.035       0  5100.0    0.07       0
Bank Sta=5016.6,5024.4
Exp/Cntr=0.3,0.1

Type RM Length L Ch R = 1,15352,341,341,341
BEGIN DESCRIPTION:
Mapping XS cd258952
END DESCRIPTION:
XS GIS Cut Line= 3
      1695264.22      7039003.45      1695272.90      7039564.22
      1695309.36      7040250.02
#Sta/Elev= 30
  4447.7 1549.02  4522.0 1543.56  4550.7 1541.02  4562.3 1539.17  4582.3 1537.60
  4642.3 1534.27  4672.3 1531.50  4732.3 1528.64  4802.3 1521.28  4825.3 1520.32
  4882.3 1518.28  4892.3 1515.96  4902.3 1514.82  5002.3 1514.19  5018.4 1513.29
  5018.9 1512.79  5026.3 1513.29  5044.4 1513.53  5074.6 1514.10  5112.5 1516.26
  5122.5 1515.68  5132.5 1516.43  5139.9 1517.93  5282.7 1523.59  5314.1 1525.47
  5402.9 1528.74  5513.0 1535.11  5593.1 1540.72  5623.2 1544.35  5695.3 1549.84
#Mann=9,-1,0
  4447.7    0.07       0  4522.0   0.035       0  4550.7    0.07       0
  4825.3   0.035       0  5018.4   0.035       0  5026.3   0.035       0
  5044.4    0.07       0  5074.6   0.035       0  5314.1    0.07       0
Bank Sta=5018.4,5026.3
Exp/Cntr=0.3,0.1

Type RM Length L Ch R = 1,15011,748,748,748
BEGIN DESCRIPTION:
Mapping XS d47663c8
END DESCRIPTION:
XS GIS Cut Line= 3
      1694949.08      7039027.40      1694975.13      7039544.77
      1695015.06      7040211.45
#Sta/Elev= 30
  4488.5 1558.54  4529.2 1554.92  4619.3 1550.97  4629.3 1549.27  4669.3 1546.23
  4729.4 1540.01  4759.4 1538.43  4769.5 1537.34  4789.5 1533.28  4819.5 1530.75
  4839.5 1527.39  4889.6 1514.76  4899.6 1513.07  4904.6 1513.43  4929.7 1510.95
  4975.6 1509.26  4976.1 1508.76  4983.8 1509.26  4989.7 1509.56  5005.6 1513.27
  5072.8 1515.67  5200.1 1519.08  5220.1 1518.52  5270.2 1520.98  5355.8 1526.87
  5390.4 1529.30  5470.6 1532.49  5587.8 1540.79  5610.8 1541.52  5674.4 1547.24
#Mann=5,-1,0
  4488.5    0.07       0  4975.6    0.07       0  4983.8    0.07       0
  5072.8   0.035       0  5355.8    0.07       0
Bank Sta=4975.6,4983.8
Exp/Cntr=0.3,0.1

Type RM Length L Ch R = 1,14263,289,289,289
BEGIN DESCRIPTION:
Mapping XS 5adbbde0
END DESCRIPTION:
XS GIS Cut Line= 3
      1694429.56      7038959.68      1694316.71      7039597.73
      1694334.07      7040359.48
#Sta/Elev= 30
  4362.1 1552.36  4401.0 1551.19  4416.6 1549.18  4461.9 1546.64  4512.7 1540.53
  4563.5 1537.92  4589.1 1534.21  4695.5 1528.89  4726.0 1525.25  4827.5 1518.76
  4868.2 1517.60  4879.8 1516.45  4918.9 1508.45  4959.5 1507.68  4990.8 1503.91
  4996.0 1503.35  4996.5 1502.85  5004.3 1503.35  5007.6 1504.59  5080.3 1509.92
  5155.0 1510.28  5300.4 1513.48  5340.4 1519.71  5390.4 1525.07  5440.4 1532.28
  5470.4 1534.26  5490.4 1538.62  5520.5 1541.87  5540.5 1545.69  5772.0 1558.13
#Mann=4,-1,0
  4362.1    0.07       0  4990.8   0.035       0  4996.0   0.035       0
  5004.3   0.035       0
Bank Sta=4996,5004.3
Exp/Cntr=0.3,0.1

Type RM Length L Ch R = 1,13974,271,271,271
BEGIN DESCRIPTION:
Mapping XS b3ceacfe
END DESCRIPTION:
XS GIS Cut Line= 3
      1694308.44      7038870.33      1694027.21      7039592.52
      1694037.63      7040273.03
#Sta/Elev= 30
  4230.0 1551.25  4278.3 1549.72  4377.7 1544.42  4417.0 1539.86  4463.6 1537.08
  4485.1 1532.44  4538.7 1529.35  4592.4 1523.70  4646.0 1519.72  4718.8 1515.82
  4742.6 1515.79  4754.0 1514.20  4866.0 1510.11  4947.0 1508.19  4957.2 1507.30
  4966.2 1503.91  4971.5 1505.27  4974.5 1503.22  4975.0 1502.72  4982.8 1503.22
  5030.5 1503.79  5040.5 1505.83  5150.5 1506.97  5240.5 1511.13  5510.6 1532.98
  5520.6 1534.38  5540.6 1539.19  5580.6 1543.23  5620.6 1545.56  5685.6 1546.93
#Mann=4,-1,0
  4230.0    0.07       0  4866.0   0.035       0  4974.5   0.035       0
  4982.8   0.035       0
Bank Sta=4974.5,4982.8
Exp/Cntr=0.3,0.1

Type RM Length L Ch R = 1,13703,373,373,373
BEGIN DESCRIPTION:
Mapping XS 52e7c9fb
END DESCRIPTION:
XS GIS Cut Line= 3
      1693650.48      7038688.03      1693775.47      7039644.60
      1693952.15      7040254.32
#Sta/Elev= 30
  4041.9 1538.02  4116.4 1535.25  4142.7 1530.07  4223.4 1524.31  4302.6 1516.40
  4348.2 1514.28  4384.8 1508.66  4418.9 1509.22  4463.7 1508.76  4546.1 1508.06
  4653.8 1504.72  4959.5 1506.46  4999.9 1502.63  5024.3 1503.44  5047.6 1501.29
  5048.1 1500.79  5055.9 1501.29  5083.0 1501.89  5091.5 1504.85  5096.7 1503.54
  5103.8 1507.30  5130.3 1514.21  5135.5 1513.01  5197.4 1519.24  5202.6 1518.49
  5308.6 1531.06  5437.0 1532.92  5458.5 1534.57  5492.1 1540.20  5641.4 1543.85
#Mann=6,-1,0
  4041.9    0.07       0  4302.6   0.035       0  4418.9    0.07       0
  4463.7   0.035       0  5047.6   0.035       0  5055.9   0.035       0
Bank Sta=5047.6,5055.9
Exp/Cntr=0.3,0.1

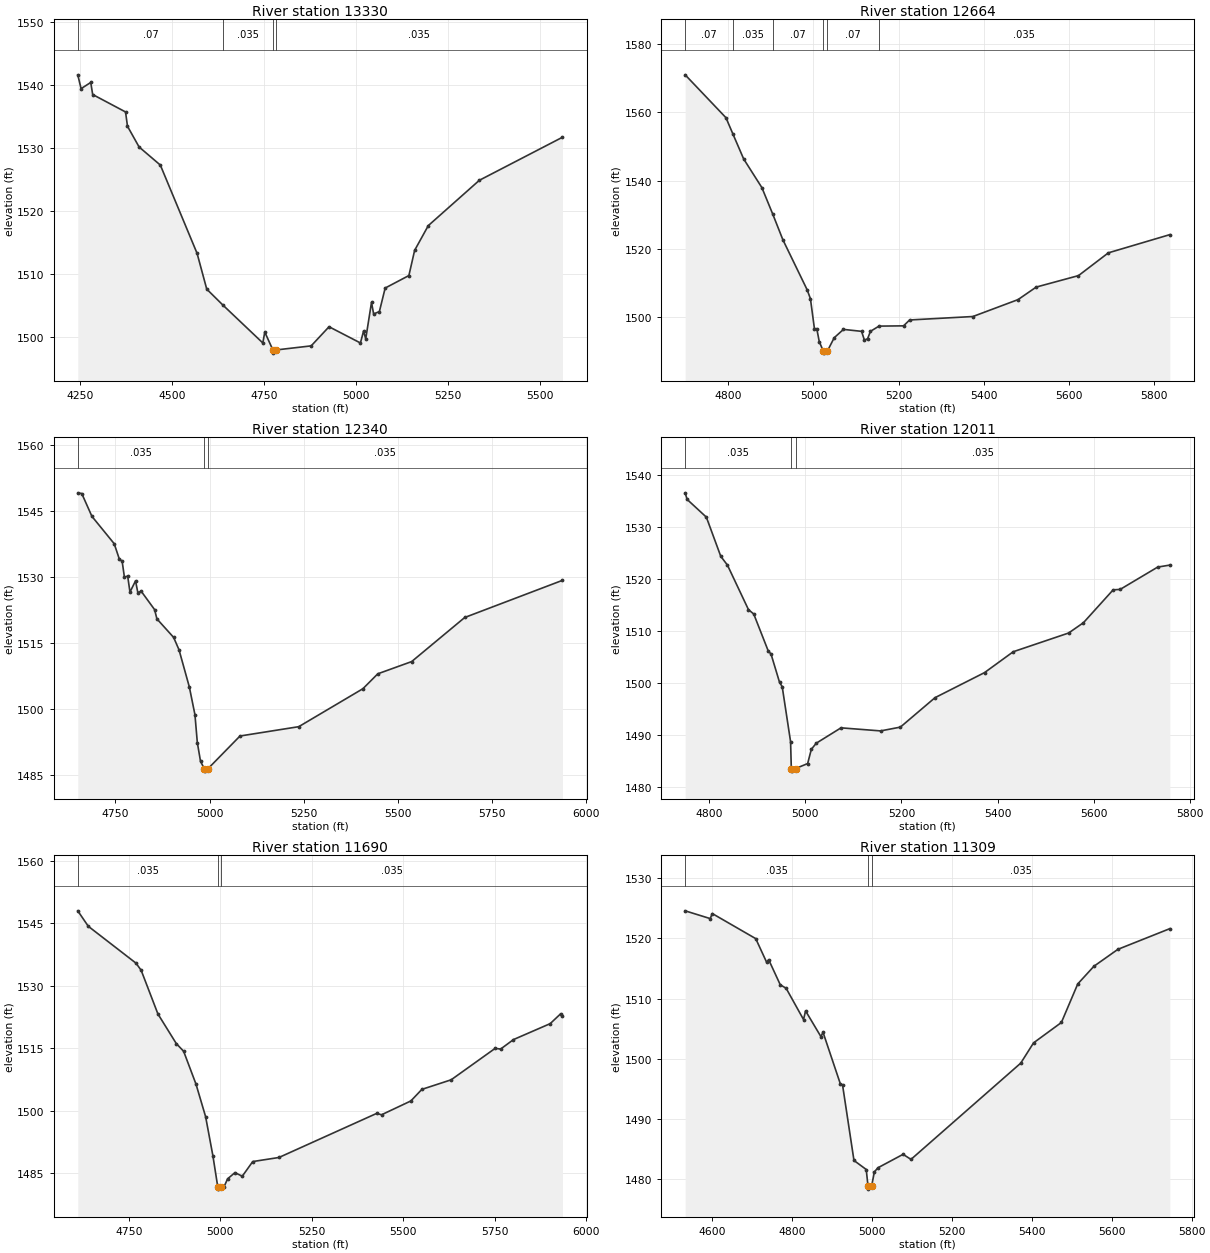
Type RM Length L Ch R = 1,13330,666,666,666
BEGIN DESCRIPTION:
Mapping XS 8ca2e478
END DESCRIPTION:
XS GIS Cut Line= 3
      1693218.19      7038771.35      1693461.24      7039493.56
      1693742.47      7039970.97
#Sta/Elev= 30
  4243.9 1541.60  4252.9 1539.41  4279.1 1540.39  4284.4 1538.48  4373.6 1535.72
  4378.9 1533.45  4410.4 1530.17  4468.1 1527.30  4567.9 1513.31  4594.1 1507.65
  4638.2 1505.11  4746.4 1499.12  4751.7 1500.85  4773.7 1498.01  4774.2 1497.51
  4782.0 1498.01  4877.7 1498.66  4926.2 1501.69  5011.4 1499.12  5020.0 1501.02
  5025.8 1499.77  5041.5 1505.55  5047.3 1503.71  5062.9 1504.10  5078.6 1507.82
  5143.0 1509.80  5158.6 1513.79  5195.7 1517.71  5334.3 1524.89  5560.0 1531.71
#Mann=4,-1,0
  4243.9    0.07       0  4638.2   0.035       0  4773.7   0.035       0
  4782.0   0.035       0
Bank Sta=4773.7,4782
Exp/Cntr=0.3,0.1

Type RM Length L Ch R = 1,12664,324,324,324
BEGIN DESCRIPTION:
Mapping XS 6552df5f
END DESCRIPTION:
XS GIS Cut Line= 3
      1692681.28      7039097.24      1692911.77      7039295.17
      1693532.83      7039853.74
#Sta/Elev= 30
  4698.4 1570.96  4794.2 1558.41  4811.0 1553.52  4835.9 1546.32  4878.7 1537.93
  4904.2 1530.18  4928.0 1522.67  4985.1 1508.00  4992.8 1505.40  5002.2 1496.62
  5007.7 1496.62  5013.6 1492.80  5023.4 1489.96  5023.9 1489.46  5032.2 1489.96
  5048.7 1493.97  5070.4 1496.41  5113.0 1495.84  5119.7 1493.25  5127.2 1493.69
  5133.9 1495.85  5154.0 1497.37  5211.7 1497.45  5225.9 1499.17  5374.6 1500.18
  5480.7 1505.13  5523.4 1508.80  5622.8 1512.16  5693.0 1518.83  5837.5 1524.16
#Mann=6,-1,0
  4698.4    0.07       0  4811.0   0.035       0  4904.2    0.07       0
  5023.4    0.07       0  5032.2    0.07       0  5154.0   0.035       0
Bank Sta=5023.4,5032.2
Exp/Cntr=0.3,0.1

Type RM Length L Ch R = 1,12340,329,329,329
BEGIN DESCRIPTION:
Mapping XS a04db3af
END DESCRIPTION:
XS GIS Cut Line= 3
      1692514.17      7039385.00      1692801.96      7039585.54
      1693645.68      7039995.68
#Sta/Elev= 30
  4649.7 1549.20  4660.3 1549.04  4687.3 1543.85  4746.6 1537.62  4760.4 1534.08
  4767.6 1533.68  4773.7 1530.04  4782.4 1530.25  4788.5 1526.63  4803.3 1529.17
  4809.4 1526.51  4818.2 1526.83  4854.0 1522.63  4860.1 1520.53  4904.6 1516.31
  4918.9 1513.50  4946.4 1505.03  4961.3 1498.73  4967.6 1492.40  4976.1 1488.13
  4986.5 1486.39  4987.0 1485.89  4995.4 1486.39  5081.1 1493.88  5237.3 1496.00
  5408.0 1504.64  5447.6 1508.03  5537.6 1510.81  5678.7 1520.84  5938.6 1529.29
#Mann=3,-1,0
  4649.7   0.035       0  4986.5   0.035       0  4995.4   0.035       0
Bank Sta=4986.5,4995.4
Exp/Cntr=0.3,0.1

Type RM Length L Ch R = 1,12011,321,321,321
BEGIN DESCRIPTION:
Mapping XS 120be95b
END DESCRIPTION:
XS GIS Cut Line= 3
      1692474.70      7039782.15      1692705.17      7039883.71
      1693439.57      7040056.90
#Sta/Elev= 30
  4751.0 1536.54  4755.0 1535.28  4795.0 1531.87  4824.9 1524.36  4838.8 1522.66
  4882.5 1514.11  4893.4 1513.28  4923.7 1506.14  4929.2 1505.62  4947.0 1500.16
  4952.5 1499.33  4969.9 1488.76  4971.4 1483.62  4971.9 1483.12  4980.3 1483.62
  5005.3 1484.57  5013.0 1487.31  5023.2 1488.48  5074.6 1491.43  5156.8 1490.84
  5197.9 1491.57  5269.8 1497.22  5372.6 1502.03  5432.3 1506.04  5547.2 1509.63
  5578.0 1511.61  5639.7 1517.92  5654.2 1518.00  5732.2 1522.29  5757.4 1522.67
#Mann=3,-1,0
  4751.0   0.035       0  4971.4   0.035       0  4980.3   0.035       0
Bank Sta=4971.4,4980.3
Exp/Cntr=0.3,0.1

Type RM Length L Ch R = 1,11690,381,381,381
BEGIN DESCRIPTION:
Mapping XS 1e18ec9a
END DESCRIPTION:
XS GIS Cut Line= 3
      1692266.38      7040161.49      1692655.26      7040187.53
      1693588.56      7040243.05
#Sta/Elev= 30
  4610.6 1548.01  4639.3 1544.30  4769.6 1535.45  4783.7 1533.76  4829.7 1523.23
  4879.8 1516.14  4899.9 1514.28  4933.7 1506.39  4960.0 1498.57  4980.0 1489.14
  4993.3 1481.67  4993.8 1481.17  5002.2 1481.67  5010.1 1481.68  5020.1 1483.65
  5040.2 1485.13  5060.2 1484.27  5088.8 1487.79  5160.4 1488.77  5427.6 1499.36
  5440.9 1499.03  5521.0 1502.35  5551.1 1505.13  5631.2 1507.43  5751.4 1514.98
  5766.3 1514.81  5801.5 1517.09  5901.7 1520.91  5930.6 1523.30  5935.3 1522.85
#Mann=3,-1,0
  4610.6   0.035       0  4993.3   0.035       0  5002.2   0.035       0
Bank Sta=4993.3,5002.2
Exp/Cntr=0.3,0.1

Type RM Length L Ch R = 1,11309,333,333,333
BEGIN DESCRIPTION:
Mapping XS 563af087
END DESCRIPTION:
XS GIS Cut Line= 3
      1692302.62      7040637.41      1692757.45      7040536.72
      1693491.77      7040399.91
#Sta/Elev= 30
  4532.6 1524.57  4595.3 1523.28  4600.4 1524.12  4709.2 1519.95  4736.4 1516.03
  4741.5 1516.46  4770.6 1512.28  4785.2 1511.71  4828.8 1506.51  4833.9 1507.95
  4872.4 1503.66  4877.5 1504.41  4921.1 1495.79  4926.3 1495.69  4955.0 1483.10
  4985.7 1481.60  4990.1 1478.84  4990.6 1478.34  4999.1 1478.84  5006.1 1481.21
  5015.0 1481.89  5077.9 1484.12  5097.7 1483.28  5372.3 1499.27  5404.4 1502.64
  5474.0 1506.02  5515.0 1512.43  5555.4 1515.36  5615.3 1518.17  5745.4 1521.61
#Mann=3,-1,0
  4532.6   0.035       0  4990.1   0.035       0  4999.1   0.035       0
Bank Sta=4990.1,4999.1
Exp/Cntr=0.3,0.1

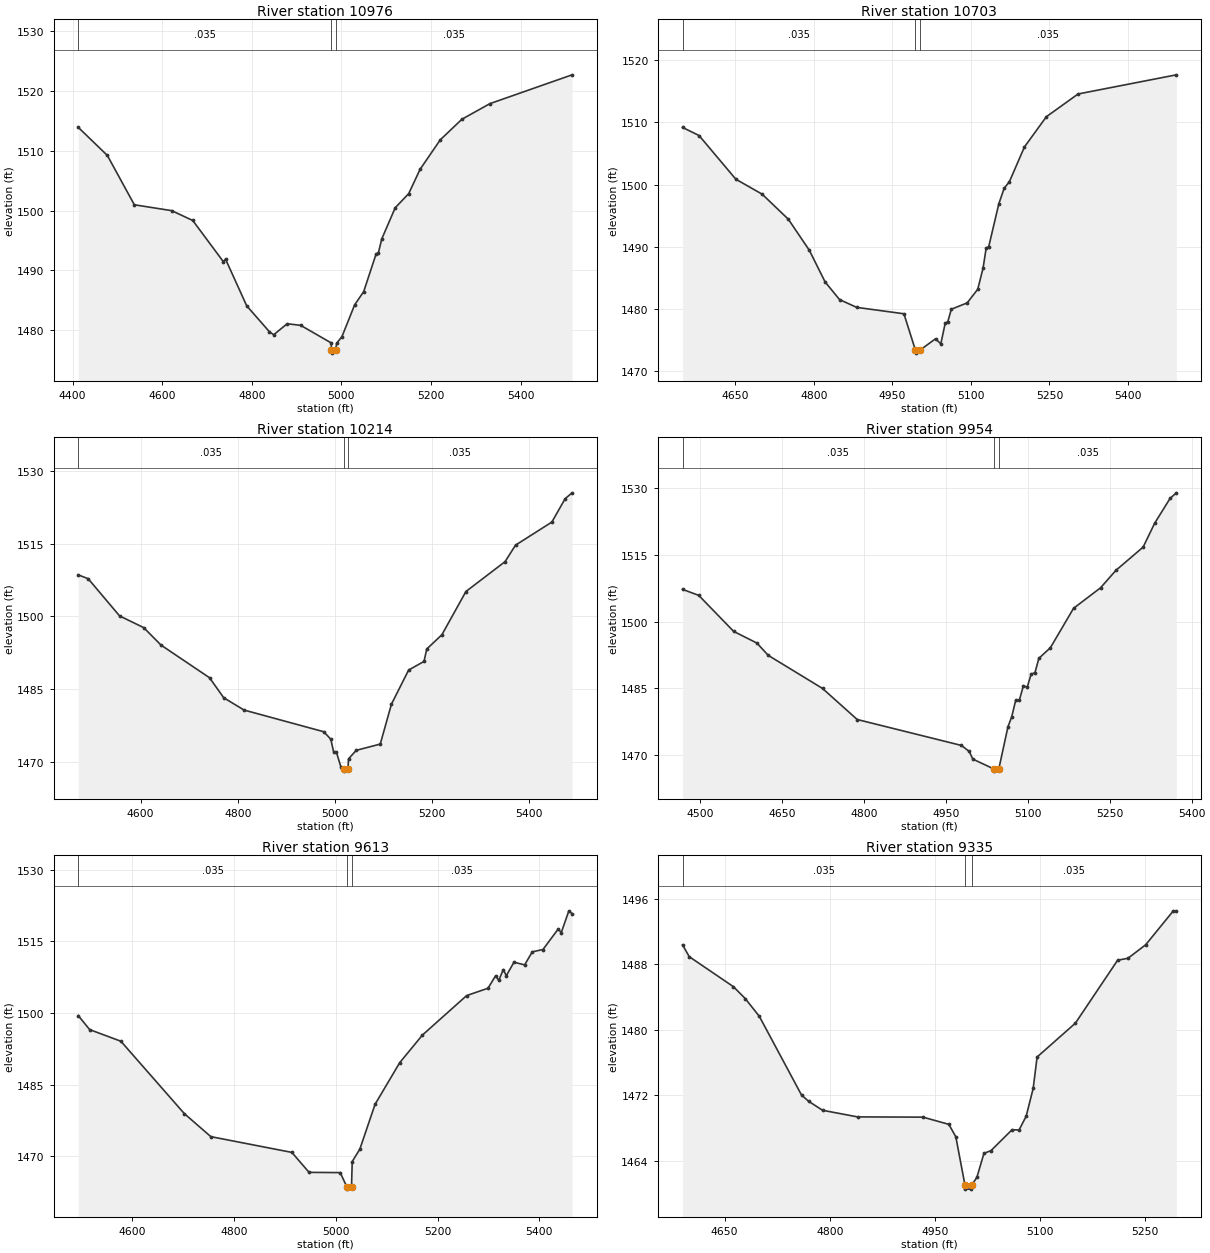
Type RM Length L Ch R = 1,10976,273,273,273
BEGIN DESCRIPTION:
Mapping XS 74d21ab8
END DESCRIPTION:
XS GIS Cut Line= 3
      1692370.26      7040830.13      1692953.64      7040781.51
      1693467.53      7040727.69
#Sta/Elev= 30
  4412.7 1513.94  4477.7 1509.23  4537.9 1500.97  4621.1 1499.99  4668.3 1498.34
  4736.5 1491.45  4741.5 1491.86  4788.7 1484.05  4838.9 1479.75  4848.9 1479.21
  4879.0 1481.05  4909.2 1480.78  4977.3 1477.84  4977.8 1476.63  4978.3 1476.13
  4986.9 1476.63  4989.4 1477.78  5001.3 1478.90  5029.6 1484.22  5049.7 1486.42
  5077.4 1492.72  5082.4 1492.86  5090.0 1495.24  5120.1 1500.47  5150.3 1502.85
  5175.6 1506.91  5220.7 1511.85  5268.9 1515.29  5331.3 1517.90  5514.8 1522.73
#Mann=3,-1,0
  4412.7   0.035       0  4977.8   0.035       0  4986.9   0.035       0
Bank Sta=4977.8,4986.9
Exp/Cntr=0.3,0.1

Type RM Length L Ch R = 1,10703,489,489,489
BEGIN DESCRIPTION:
Mapping XS 76dcbb37
END DESCRIPTION:
XS GIS Cut Line= 3
      1692463.49      7041079.22      1692912.75      7041040.15
      1693401.20      7040975.20
#Sta/Elev= 30
  4548.9 1509.19  4580.5 1507.89  4650.8 1500.86  4701.0 1498.46  4751.2 1494.42
  4791.3 1489.42  4821.4 1484.34  4849.0 1481.50  4881.7 1480.25  4972.0 1479.22
  4993.9 1473.39  4994.4 1472.89  5003.0 1473.39  5032.4 1475.20  5042.5 1474.38
  5050.8 1477.67  5055.9 1477.97  5062.6 1479.95  5092.9 1480.97  5113.1 1483.17
  5123.2 1486.54  5129.1 1489.74  5134.1 1490.03  5153.4 1496.92  5163.5 1499.39
  5173.6 1500.47  5202.3 1506.05  5244.2 1510.91  5304.8 1514.57  5492.6 1517.65
#Mann=3,-1,0
  4548.9   0.035       0  4993.9   0.035       0  5003.0   0.035       0
Bank Sta=4993.9,5003
Exp/Cntr=0.3,0.1

Type RM Length L Ch R = 1,10214,260,260,260
BEGIN DESCRIPTION:
Mapping XS 0db769be
END DESCRIPTION:
XS GIS Cut Line= 3
      1692443.14      7041160.97      1692864.12      7041479.97
      1693287.30      7041723.02
#Sta/Elev= 30
  4471.7 1508.55  4492.2 1507.75  4556.7 1500.10  4606.6 1497.67  4642.0 1494.09
  4741.9 1487.36  4771.0 1483.25  4812.8 1480.71  4977.0 1476.24  4991.5 1474.69
  4997.3 1472.05  5002.9 1472.05  5012.4 1468.93  5017.6 1468.63  5018.1 1468.13
  5026.7 1468.63  5027.9 1470.66  5043.7 1472.41  5093.2 1473.70  5116.2 1481.92
  5151.6 1488.95  5183.2 1490.72  5188.9 1493.28  5220.0 1496.21  5269.5 1505.12
  5350.0 1511.27  5371.5 1514.66  5446.3 1519.42  5473.7 1524.24  5487.9 1525.44
#Mann=3,-1,0
  4471.7   0.035       0  5017.6   0.035       0  5026.7   0.035       0
Bank Sta=5017.6,5026.7
Exp/Cntr=0.3,0.1

Type RM Length L Ch R = 1,9954,341,341,341
BEGIN DESCRIPTION:
Mapping XS 830d6624
END DESCRIPTION:
XS GIS Cut Line= 3
      1692382.34      7041308.51      1692749.10      7041696.98
      1693014.91      7041954.15
#Sta/Elev= 30
  4467.9 1507.26  4497.6 1505.91  4561.5 1497.82  4604.0 1495.20  4625.0 1492.42
  4724.2 1485.00  4787.7 1478.02  4978.6 1472.19  4992.8 1470.84  4999.4 1469.12
  5037.7 1466.92  5038.2 1466.42  5047.0 1466.92  5063.7 1476.39  5070.7 1478.66
  5077.8 1482.31  5084.8 1482.47  5092.0 1485.63  5098.9 1485.24  5106.1 1488.21
  5113.1 1488.53  5120.3 1491.76  5141.4 1494.15  5183.8 1503.00  5233.2 1507.61
  5261.5 1511.55  5311.2 1516.76  5332.3 1522.12  5360.6 1527.72  5372.0 1528.95
#Mann=3,-1,0
  4467.9   0.035       0  5037.7   0.035       0  5047.0   0.035       0
Bank Sta=5037.7,5047
Exp/Cntr=0.3,0.1

Type RM Length L Ch R = 1,9613,278,278,278
BEGIN DESCRIPTION:
Mapping XS e41a628f
END DESCRIPTION:
XS GIS Cut Line= 3
      1692365.00      7041447.45      1692506.05      7041940.04
      1692885.80      7042196.10
#Sta/Elev= 30
  4493.9 1499.45  4516.3 1496.51  4577.7 1494.07  4702.5 1478.90  4754.5 1474.09
  4913.7 1470.79  4947.5 1466.61  5008.7 1466.56  5021.6 1463.60  5022.1 1463.10
  5030.9 1463.60  5032.3 1468.88  5047.3 1471.48  5077.2 1480.87  5125.6 1489.58
  5170.2 1495.36  5257.1 1503.63  5299.1 1505.17  5314.1 1507.79  5320.2 1506.79
  5329.1 1509.08  5335.1 1507.80  5350.1 1510.62  5371.1 1510.06  5386.1 1512.79
  5407.1 1513.28  5437.0 1517.56  5443.1 1516.83  5458.0 1521.38  5464.3 1520.81
#Mann=3,-1,0
  4493.9   0.035       0  5021.6   0.035       0  5030.9   0.035       0
Bank Sta=5021.6,5030.9
Exp/Cntr=0.3,0.1

Type RM Length L Ch R = 1,9335,321,321,321
BEGIN DESCRIPTION:
Mapping XS 77db704d
END DESCRIPTION:
XS GIS Cut Line= 3
      1692227.38      7041578.45      1692242.57      7041988.65
      1692265.36      7042281.58
#Sta/Elev= 30
  4590.1 1490.40  4599.7 1488.95  4662.8 1485.27  4679.7 1483.81  4699.7 1481.64
  4759.8 1472.02  4769.8 1471.26  4789.8 1470.15  4839.8 1469.34  4933.0 1469.31
  4969.9 1468.43  4979.9 1466.90  4992.9 1461.00  4993.4 1460.50  5002.2 1460.50
  5002.7 1461.00  5010.0 1461.96  5020.0 1464.88  5030.0 1465.21  5060.1 1467.77
  5070.1 1467.74  5080.2 1469.42  5090.2 1472.82  5095.8 1476.67  5150.4 1480.81
  5210.6 1488.51  5225.5 1488.76  5250.7 1490.41  5290.1 1494.56  5294.4 1494.56
#Mann=3,-1,0
  4590.1   0.035       0  4992.9   0.035       0  5002.7   0.035       0
Bank Sta=4992.9,5002.7
Exp/Cntr=0.3,0.1

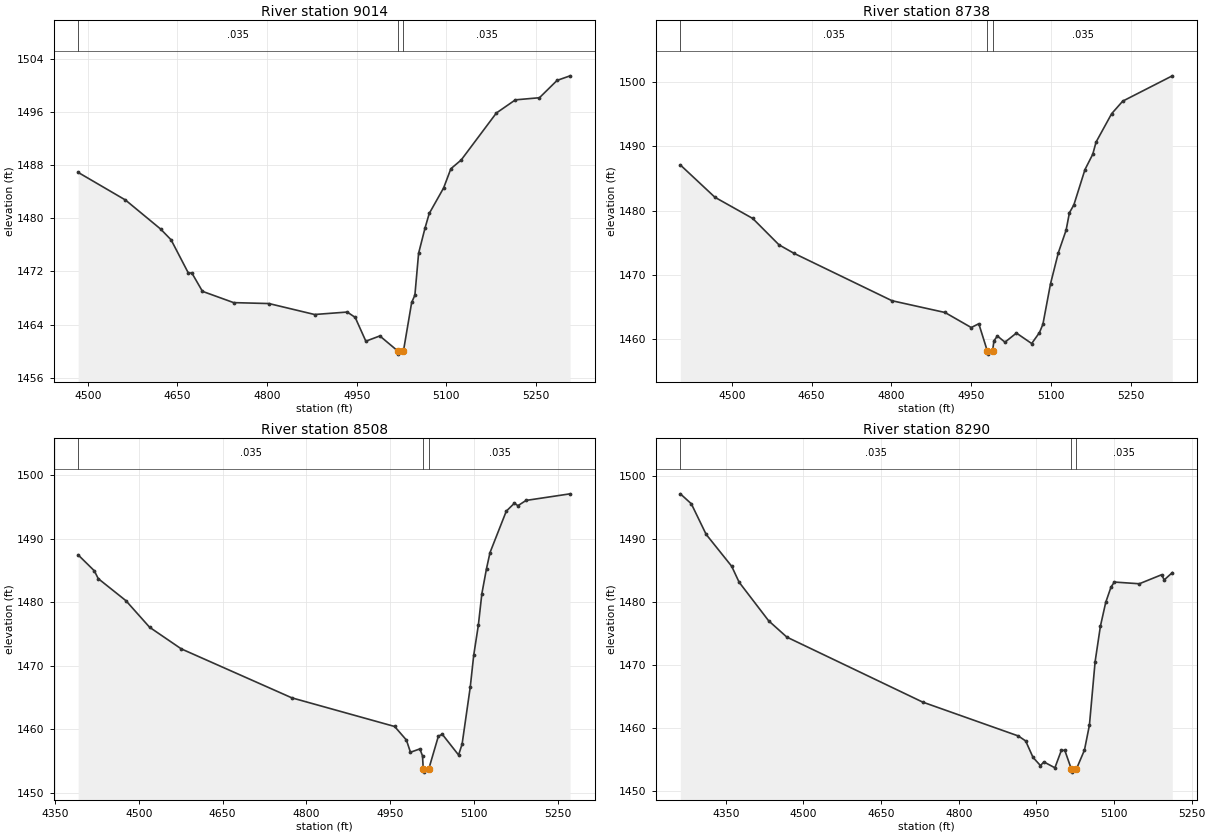
Type RM Length L Ch R = 1,9014,276,276,276
BEGIN DESCRIPTION:
Mapping XS 02f2c320
END DESCRIPTION:
XS GIS Cut Line= 3
      1692144.91      7041565.50      1691936.59      7042040.73
      1691821.59      7042322.80
#Sta/Elev= 30
  4483.8 1486.92  4563.0 1482.76  4621.8 1478.39  4639.4 1476.76  4668.5 1471.72
  4674.0 1471.79  4691.9 1469.00  4744.1 1467.30  4803.2 1467.16  4879.6 1465.51
  4934.2 1465.88  4947.5 1465.08  4965.4 1461.49  4988.8 1462.28  5018.5 1460.04
  5019.0 1459.54  5028.4 1460.04  5042.1 1467.32  5047.5 1468.43  5053.7 1474.73
  5064.5 1478.55  5071.5 1480.73  5095.6 1484.58  5107.7 1487.47  5125.0 1488.79
  5183.9 1495.87  5215.7 1497.85  5256.0 1498.17  5285.5 1500.78  5307.3 1501.47
#Mann=3,-1,0
  4483.8   0.035       0  5018.5   0.035       0  5028.4   0.035       0
Bank Sta=5018.5,5028.4
Exp/Cntr=0.3,0.1

Type RM Length L Ch R = 1,8738,230,230,230
BEGIN DESCRIPTION:
Mapping XS 97a43784
END DESCRIPTION:
XS GIS Cut Line= 3
      1692112.39      7041503.60      1691714.15      7041952.84
      1691521.50      7042213.67
#Sta/Elev= 30
  4403.4 1487.12  4468.4 1482.09  4539.5 1478.79  4588.8 1474.69  4617.2 1473.36
  4801.2 1465.99  4900.8 1464.16  4950.1 1461.82  4964.3 1462.41  4980.3 1458.18
  4980.8 1457.68  4990.2 1458.18  4992.8 1459.76  4999.3 1460.50  5013.5 1459.54
  5035.0 1460.96  5063.7 1459.33  5078.3 1461.03  5084.8 1462.33  5099.1 1468.63
  5113.8 1473.46  5128.4 1476.97  5134.6 1479.67  5143.0 1480.91  5163.9 1486.41
  5178.5 1488.79  5184.7 1490.68  5214.0 1495.10  5234.8 1497.05  5328.0 1500.99
#Mann=3,-1,0
  4403.4   0.035       0  4980.3   0.035       0  4990.2   0.035       0
Bank Sta=4980.3,4990.2
Exp/Cntr=0.3,0.1

Type RM Length L Ch R = 1,8508,218,218,218
BEGIN DESCRIPTION:
Mapping XS 92cb296b
END DESCRIPTION:
XS GIS Cut Line= 3
      1691969.67      7041391.76      1691534.53      7041821.47
      1691372.87      7042036.29
#Sta/Elev= 30
  4391.6 1487.49  4420.5 1484.99  4427.6 1483.75  4477.1 1480.28  4519.5 1476.09
  4576.1 1472.69  4774.1 1464.97  4958.0 1460.46  4979.1 1458.32  4986.3 1456.40
  5003.2 1456.93  5007.9 1455.82  5009.2 1453.77  5009.7 1453.27  5019.1 1453.77
  5036.3 1458.94  5043.3 1459.23  5072.4 1455.97  5078.7 1457.67  5093.3 1466.65
  5099.5 1471.67  5107.8 1476.41  5114.1 1481.38  5122.4 1485.33  5128.7 1487.86
  5157.8 1494.38  5172.4 1495.64  5178.6 1495.24  5193.2 1496.07  5272.0 1497.11
#Mann=3,-1,0
  4391.6   0.035       0  5009.2   0.035       0  5019.1   0.035       0
Bank Sta=5009.2,5019.1
Exp/Cntr=0.3,0.1

Type RM Length L Ch R = 1,8290,188,188,188
BEGIN DESCRIPTION:
Mapping XS 5e2fa1ff
END DESCRIPTION:
XS GIS Cut Line= 3
      1691926.23      7041219.27      1691362.00      7041698.86
      1691315.46      7041903.42
#Sta/Elev= 30
  4262.2 1497.19  4283.4 1495.61  4312.0 1490.76  4361.4 1485.69  4375.7 1483.17
  4432.8 1477.04  4468.0 1474.45  4730.4 1464.14  4915.0 1458.77  4929.2 1457.98
  4943.5 1455.36  4957.8 1454.07  4964.4 1454.65  4985.7 1453.72  4998.2 1456.49
  5004.8 1456.49  5017.4 1453.53  5017.9 1453.03  5027.3 1453.53  5042.8 1456.53
  5052.4 1460.49  5063.4 1470.57  5073.6 1476.18  5083.9 1479.97  5094.1 1482.40
  5100.6 1483.19  5148.8 1482.92  5191.8 1484.35  5196.9 1483.53  5212.5 1484.69
#Mann=3,-1,0
  4262.2   0.035       0  5017.4   0.035       0  5027.3   0.035       0
Bank Sta=5017.4,5027.3
Exp/Cntr=0.3,0.1