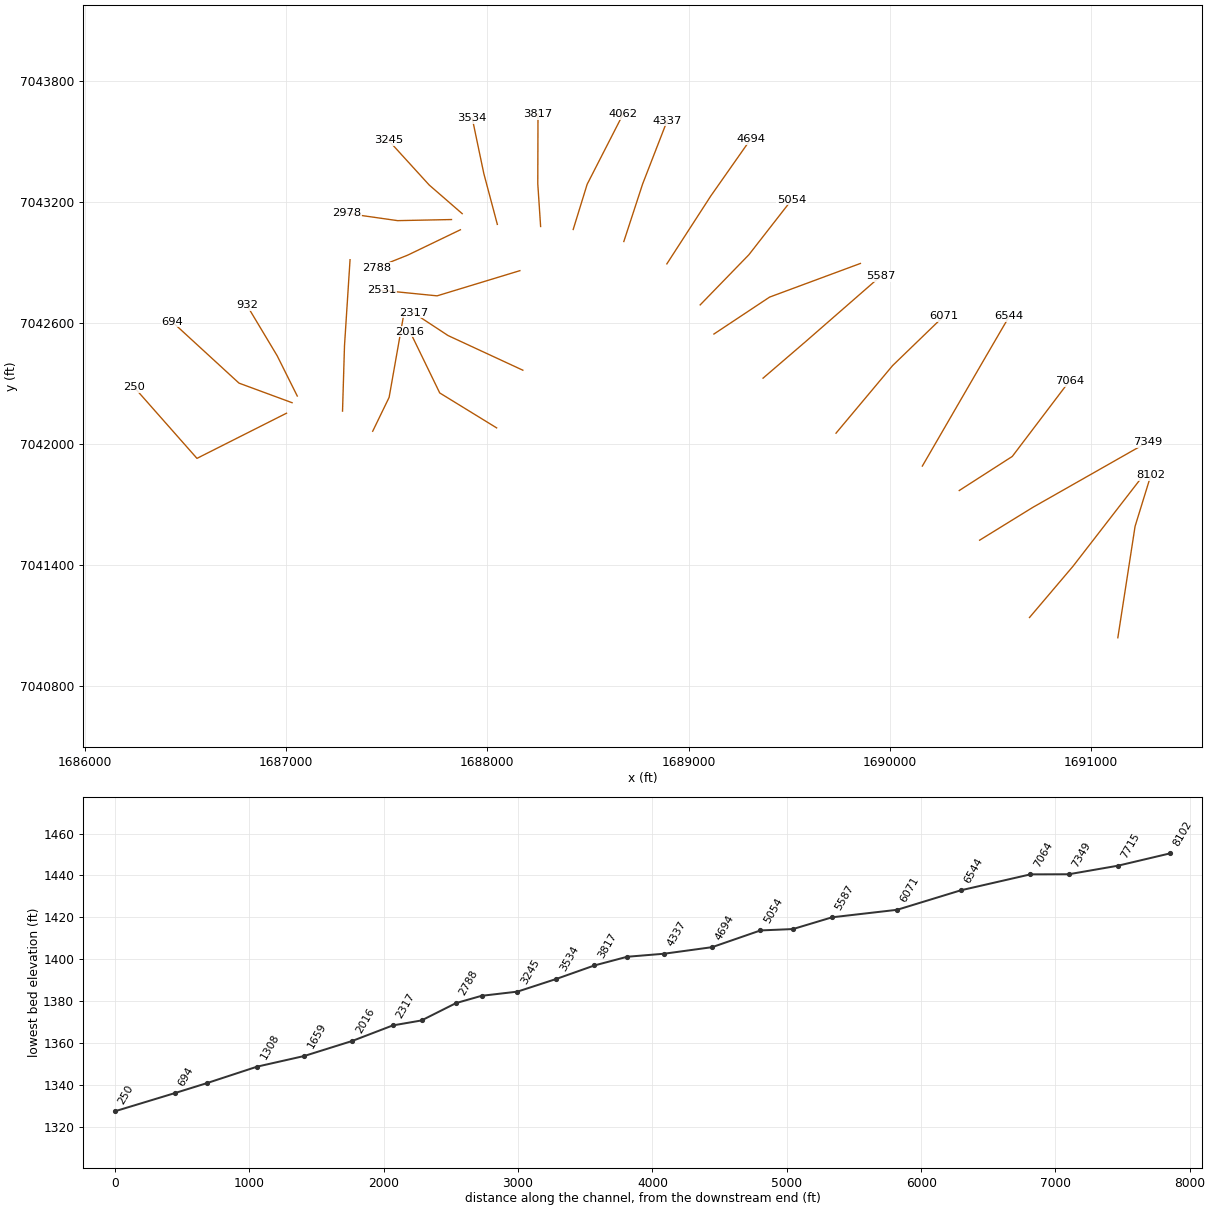
HEC-RAS study Chimney Creek 1192.prj: Chimney Creek 1192 Base Level Engineering

--- Chimney Creek 1192.g01 (geometry) --- (continued)

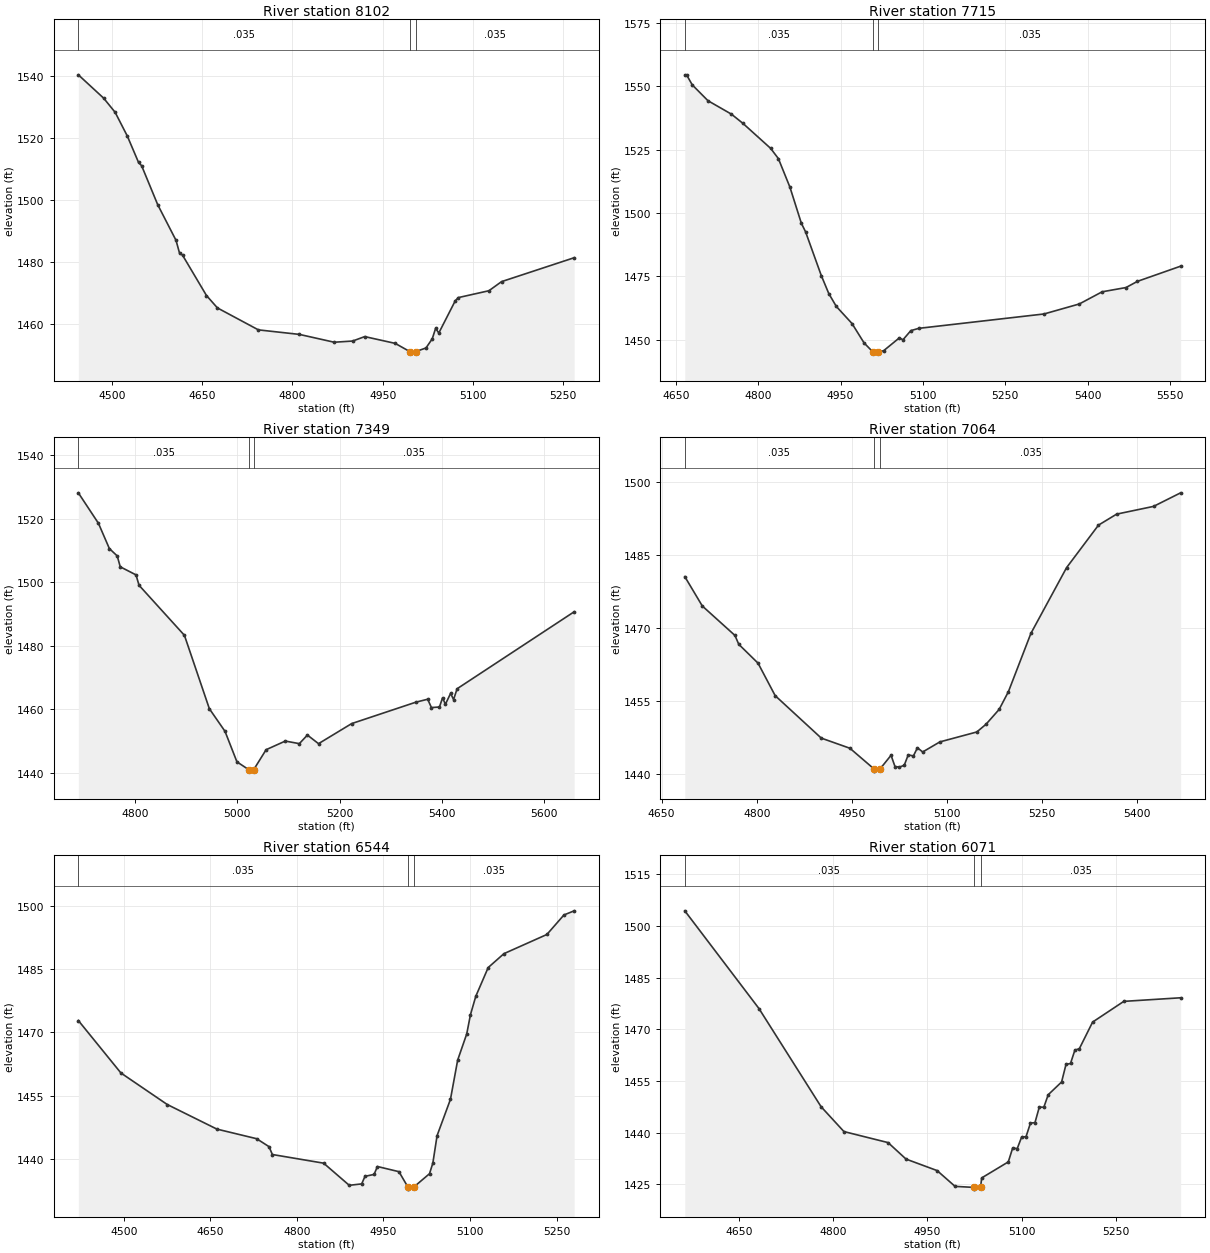
Type RM Length L Ch R = 1,8102,387,387,387
BEGIN DESCRIPTION:
Mapping XS fa4cd478
END DESCRIPTION:
XS GIS Cut Line= 3
      1691134.14      7041037.52      1691219.86      7041590.90
      1691297.87      7041843.34
#Sta/Elev= 30
  4444.0 1540.42  4486.1 1532.88  4505.2 1528.31  4525.4 1520.66  4544.1 1512.12
  4549.2 1511.07  4576.0 1498.46  4606.4 1486.96  4612.2 1482.86  4617.2 1482.18
  4657.0 1469.15  4675.2 1465.14  4743.3 1458.05  4811.4 1456.59  4869.3 1454.06
  4899.9 1454.44  4920.1 1455.88  4970.7 1453.69  4995.0 1451.04  4995.5 1450.54
  5005.0 1451.04  5021.9 1452.21  5032.3 1455.16  5037.9 1458.54  5043.2 1457.04
  5070.6 1467.46  5075.8 1468.48  5126.5 1470.69  5147.5 1473.63  5268.2 1481.35
#Mann=3,-1,0
  4444.0   0.035       0  4995.0   0.035       0  5005.0   0.035       0
Bank Sta=4995,5005
Exp/Cntr=0.3,0.1

Type RM Length L Ch R = 1,7715,366,366,366
BEGIN DESCRIPTION:
Mapping XS 0bf09283
END DESCRIPTION:
XS GIS Cut Line= 3
      1690695.04      7041138.08      1690911.19      7041392.44
      1691260.06      7041842.83
#Sta/Elev= 30
  4666.1 1554.48  4669.3 1554.48  4679.7 1550.51  4708.3 1544.27  4751.1 1538.96
  4772.0 1535.33  4822.5 1525.47  4836.6 1521.44  4857.7 1510.14  4878.5 1495.91
  4886.2 1492.52  4914.8 1475.29  4928.5 1468.16  4942.2 1463.09  4970.8 1456.35
  4992.8 1448.69  5008.7 1445.17  5009.2 1444.67  5018.8 1445.17  5028.3 1445.60
  5057.2 1450.71  5063.6 1449.93  5078.0 1453.55  5092.5 1454.45  5320.7 1460.12
  5385.0 1464.07  5426.6 1468.87  5470.1 1470.55  5490.9 1472.99  5569.6 1478.98
#Mann=3,-1,0
  4666.1   0.035       0  5008.7   0.035       0  5018.8   0.035       0
Bank Sta=5008.7,5018.8
Exp/Cntr=0.3,0.1

Type RM Length L Ch R = 1,7349,285,285,285
BEGIN DESCRIPTION:
Mapping XS eac66e9a
END DESCRIPTION:
XS GIS Cut Line= 3
      1690447.07      7041522.01      1690711.83      7041685.20
      1691283.90      7042009.87
#Sta/Elev= 30
  4689.3 1528.16  4728.6 1518.57  4749.9 1510.63  4765.3 1508.30  4771.2 1504.88
  4802.0 1502.34  4807.9 1499.07  4896.6 1483.32  4945.3 1460.23  4975.9 1453.11
  4999.2 1443.51  5021.9 1441.09  5022.4 1440.59  5032.1 1441.09  5056.2 1447.33
  5093.7 1450.05  5121.1 1449.24  5136.9 1451.94  5158.6 1449.23  5223.4 1455.55
  5348.9 1462.29  5371.9 1463.21  5379.2 1460.60  5394.9 1460.76  5400.9 1463.63
  5406.6 1461.65  5416.7 1465.06  5422.5 1463.10  5429.4 1466.51  5658.1 1490.73
#Mann=3,-1,0
  4689.3   0.035       0  5021.9   0.035       0  5032.1   0.035       0
Bank Sta=5021.9,5032.1
Exp/Cntr=0.3,0.1

Type RM Length L Ch R = 1,7064,520,520,520
BEGIN DESCRIPTION:
Mapping XS 2c1c3373
END DESCRIPTION:
XS GIS Cut Line= 3
      1690345.84      7041768.71      1690609.47      7041937.95
      1690892.66      7042311.20
#Sta/Elev= 30
  4686.6 1480.54  4714.2 1474.50  4765.7 1468.44  4771.7 1466.62  4802.1 1462.74
  4829.1 1456.06  4901.8 1447.33  4947.0 1445.24  4984.5 1441.04  4985.0 1440.54
  4994.8 1441.04  5011.8 1443.80  5018.0 1441.49  5025.0 1441.37  5032.6 1441.74
  5038.9 1443.88  5047.1 1443.67  5053.4 1445.34  5061.7 1444.48  5088.8 1446.55
  5147.0 1448.59  5161.5 1450.17  5182.3 1453.24  5196.9 1456.89  5232.3 1468.86
  5288.6 1482.39  5338.9 1491.13  5367.5 1493.39  5425.7 1494.98  5468.4 1497.77
#Mann=3,-1,0
  4686.6   0.035       0  4984.5   0.035       0  4994.8   0.035       0
Bank Sta=4984.5,4994.8
Exp/Cntr=0.3,0.1

Type RM Length L Ch R = 1,6544,473,473,473
BEGIN DESCRIPTION:
Mapping XS 3c0a340f
END DESCRIPTION:
XS GIS Cut Line= 3
      1690162.41      7041890.18      1690453.22      7042391.51
      1690594.15      7042633.26
#Sta/Elev= 30
  4421.2 1472.79  4495.0 1460.38  4575.3 1452.92  4661.4 1447.10  4730.2 1444.83
  4751.7 1442.95  4757.5 1441.09  4846.4 1439.04  4890.8 1433.80  4912.3 1434.14
  4918.1 1435.93  4933.8 1436.38  4939.6 1438.25  4976.9 1437.03  4992.4 1433.40
  4992.9 1432.90  5002.7 1433.40  5029.9 1436.55  5035.7 1439.08  5043.0 1445.55
  5066.2 1454.15  5078.7 1463.43  5094.4 1469.62  5100.9 1474.19  5110.1 1478.52
  5131.6 1485.32  5158.9 1488.61  5233.3 1493.14  5262.9 1497.76  5280.6 1498.74
#Mann=3,-1,0
  4421.2   0.035       0  4992.4   0.035       0  5002.7   0.035       0
Bank Sta=4992.4,5002.7
Exp/Cntr=0.3,0.1

Type RM Length L Ch R = 1,6071,484,484,484
BEGIN DESCRIPTION:
Mapping XS a5bf0946
END DESCRIPTION:
XS GIS Cut Line= 3
      1689733.16      7042053.47      1690014.20      7042388.76
      1690267.61      7042633.50
#Sta/Elev= 30
  4563.6 1504.36  4681.8 1475.99  4780.7 1447.52  4817.1 1440.31  4887.4 1437.11
  4916.0 1432.33  4965.5 1428.99  4994.1 1424.41  5024.3 1424.11  5024.8 1423.61
  5034.7 1424.11  5036.5 1426.86  5078.9 1431.51  5085.9 1435.56  5093.1 1435.36
  5100.0 1438.65  5107.2 1438.86  5114.2 1442.77  5121.4 1442.91  5128.3 1447.42
  5135.5 1447.37  5142.5 1451.00  5163.8 1454.70  5170.8 1459.78  5178.0 1460.07
  5184.9 1463.91  5192.1 1464.37  5213.2 1472.08  5262.9 1478.09  5353.4 1479.13
#Mann=3,-1,0
  4563.6   0.035       0  5024.3   0.035       0  5034.7   0.035       0
Bank Sta=5024.3,5034.7
Exp/Cntr=0.3,0.1

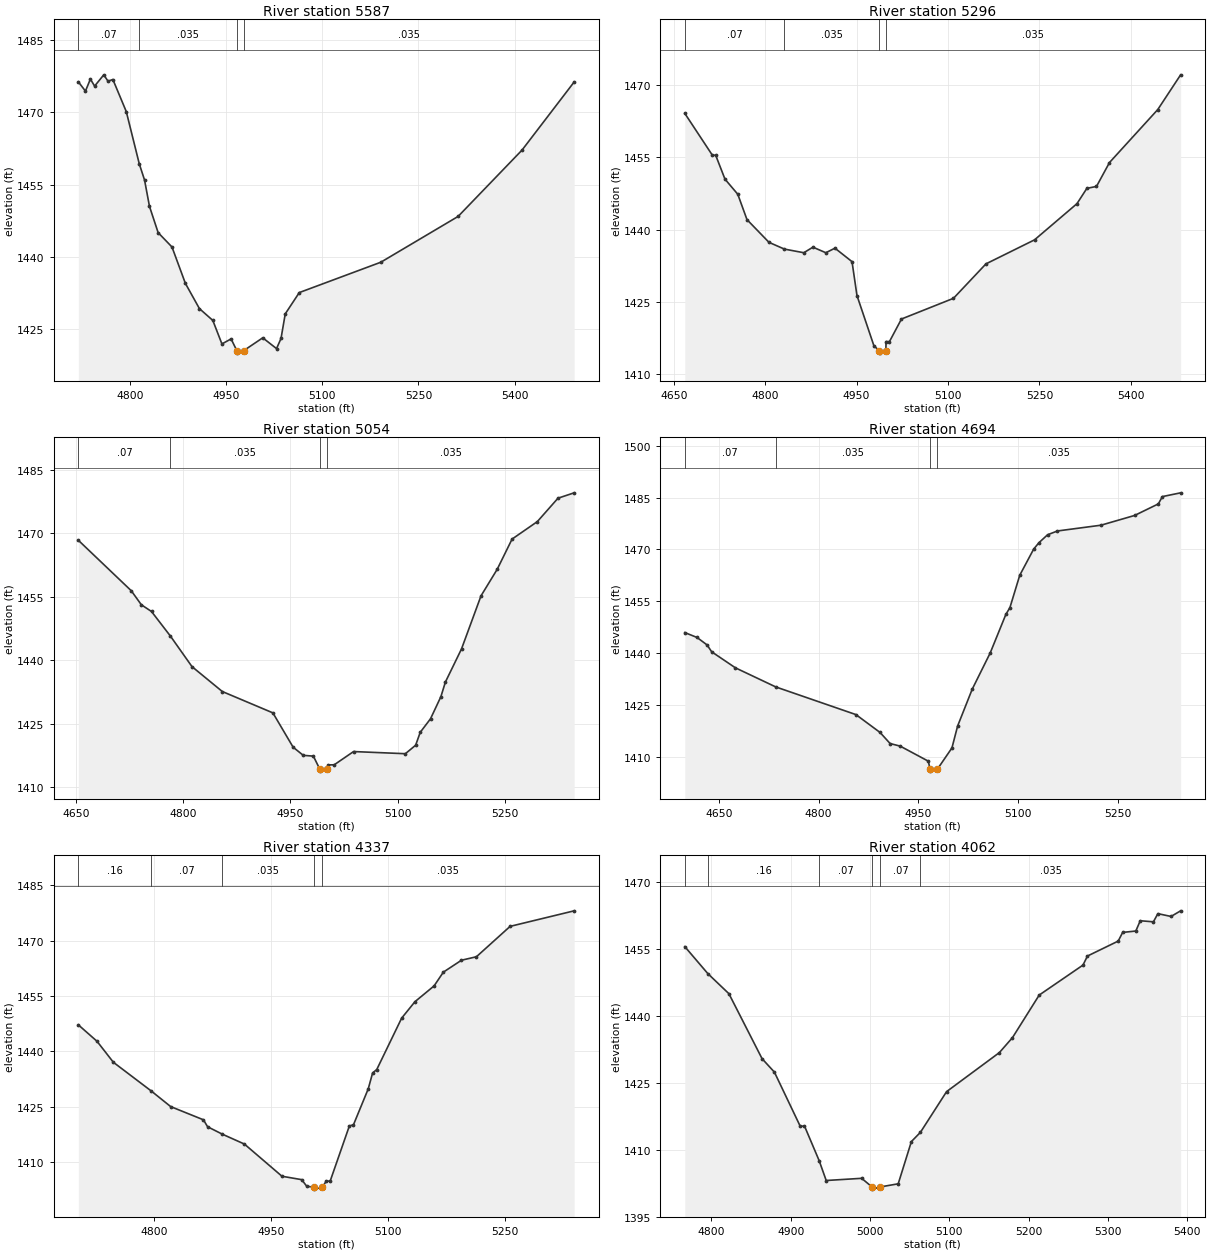
Type RM Length L Ch R = 1,5587,291,291,291
BEGIN DESCRIPTION:
Mapping XS d281d068
END DESCRIPTION:
XS GIS Cut Line= 3
      1689370.50      7042326.65      1689584.23      7042510.00
      1689955.09      7042833.15
#Sta/Elev= 30
  4719.4 1476.35  4730.5 1474.42  4738.2 1476.92  4744.8 1475.46  4759.1 1477.80
  4765.7 1476.48  4773.3 1476.83  4794.2 1470.17  4814.5 1459.31  4822.7 1455.96
  4830.4 1450.49  4843.9 1445.04  4865.5 1442.06  4886.4 1434.51  4908.3 1429.27
  4929.2 1426.82  4943.4 1421.94  4957.7 1422.98  4966.7 1420.53  4967.2 1420.03
  4977.2 1420.53  5007.1 1423.21  5028.6 1420.97  5035.6 1423.07  5042.2 1428.18
  5064.1 1432.60  5191.3 1438.90  5311.9 1448.41  5411.6 1462.18  5492.9 1476.32
#Mann=4,-1,0
  4719.4    0.07       0  4814.5   0.035       0  4966.7   0.035       0
  4977.2   0.035       0
Bank Sta=4966.7,4977.2
Exp/Cntr=0.3,0.1

Type RM Length L Ch R = 1,5296,242,242,242
BEGIN DESCRIPTION:
Mapping XS 37a741fe
END DESCRIPTION:
XS GIS Cut Line= 3
      1689126.32      7042545.81      1689403.02      7042729.19
      1689854.44      7042896.30
#Sta/Elev= 30
  4668.2 1464.11  4713.0 1455.52  4719.0 1455.39  4734.1 1450.48  4755.1 1447.35
  4770.2 1442.09  4806.3 1437.38  4831.6 1435.98  4863.4 1435.23  4878.4 1436.38
  4899.5 1435.23  4914.5 1436.17  4942.5 1433.38  4950.6 1426.36  4978.5 1415.91
  4987.5 1414.92  4988.0 1414.42  4998.0 1414.92  4998.3 1416.81  5003.9 1416.81
  5023.6 1421.49  5108.9 1425.78  5162.2 1432.92  5241.9 1437.90  5311.5 1445.40
  5327.7 1448.57  5343.5 1448.97  5364.8 1453.92  5444.0 1464.90  5481.5 1472.10
#Mann=4,-1,0
  4668.2    0.07       0  4831.6   0.035       0  4987.5   0.035       0
  4998.0   0.035       0
Bank Sta=4987.5,4998
Exp/Cntr=0.3,0.1

Type RM Length L Ch R = 1,5054,360,360,360
BEGIN DESCRIPTION:
Mapping XS 9d0b85cd
END DESCRIPTION:
XS GIS Cut Line= 3
      1689057.92      7042690.46      1689300.11      7042939.60
      1689512.80      7043212.18
#Sta/Elev= 30
  4653.4 1468.37  4727.4 1456.43  4741.5 1453.11  4755.7 1451.52  4782.2 1445.69
  4812.3 1438.48  4854.7 1432.59  4925.4 1427.54  4953.7 1419.42  4967.9 1417.49
  4982.0 1417.31  4990.9 1414.26  4991.4 1413.76  5001.5 1414.26  5003.0 1415.24
  5011.1 1415.25  5038.2 1418.39  5110.6 1417.88  5125.0 1419.89  5131.4 1422.94
  5145.8 1426.15  5160.3 1431.38  5166.6 1434.84  5189.1 1442.66  5216.4 1455.23
  5239.0 1461.50  5259.8 1468.65  5295.1 1472.78  5324.0 1478.32  5346.6 1479.59
#Mann=4,-1,0
  4653.4    0.07       0  4782.2   0.035       0  4990.9   0.035       0
  5001.5   0.035       0
Bank Sta=4990.9,5001.5
Exp/Cntr=0.3,0.1

Type RM Length L Ch R = 1,4694,357,357,357
BEGIN DESCRIPTION:
Mapping XS 2e734011
END DESCRIPTION:
XS GIS Cut Line= 3
      1688892.22      7042894.13      1689110.96      7043231.79
      1689308.00      7043512.16
#Sta/Elev= 30
  4598.9 1445.91  4617.3 1444.49  4632.4 1442.32  4639.3 1440.34  4675.0 1435.69
  4735.6 1430.16  4856.0 1422.15  4892.3 1416.97  4907.4 1413.76  4922.6 1413.01
  4964.8 1408.65  4967.5 1406.27  4968.0 1405.77  4978.2 1406.27  5000.3 1412.49
  5008.8 1418.82  5030.7 1429.48  5057.8 1440.01  5081.3 1451.16  5087.4 1453.14
  5102.2 1462.52  5123.1 1470.09  5131.0 1471.94  5144.0 1474.24  5158.8 1475.34
  5224.2 1477.01  5274.7 1479.83  5310.4 1483.18  5316.5 1485.30  5343.9 1486.39
#Mann=4,-1,0
  4598.9    0.07       0  4735.6   0.035       0  4967.5   0.035       0
  4978.2   0.035       0
Bank Sta=4967.5,4978.2
Exp/Cntr=0.3,0.1

Type RM Length L Ch R = 1,4337,275,275,275
BEGIN DESCRIPTION:
Mapping XS 8d818b14
END DESCRIPTION:
XS GIS Cut Line= 3
      1688678.38      7043005.20      1688771.70      7043290.57
      1688893.67      7043604.68
#Sta/Elev= 30
  4702.3 1447.17  4726.3 1442.72  4747.3 1437.03  4795.9 1429.26  4821.0 1425.01
  4863.1 1421.43  4868.4 1419.55  4887.5 1417.52  4915.7 1414.86  4964.0 1406.13
  4989.3 1405.21  4995.8 1403.43  5005.2 1403.14  5005.7 1402.64  5015.9 1403.14
  5020.7 1404.75  5026.0 1404.85  5050.6 1419.76  5055.9 1420.09  5074.9 1429.84
  5080.5 1434.14  5085.8 1435.05  5117.8 1448.99  5134.9 1453.45  5159.5 1457.73
  5171.4 1461.46  5194.7 1464.69  5213.9 1465.63  5257.2 1473.87  5339.5 1478.08
#Mann=5,-1,0
  4702.3    0.16       0  4795.9    0.07       0  4887.5   0.035       0
  5005.2   0.035       0  5015.9   0.035       0
Bank Sta=5005.2,5015.9
Exp/Cntr=0.3,0.1

Type RM Length L Ch R = 1,4062,245,245,245
BEGIN DESCRIPTION:
Mapping XS 1f92c016
END DESCRIPTION:
XS GIS Cut Line= 3
      1688426.66      7043064.92      1688496.09      7043289.49
      1688674.03      7043636.69
#Sta/Elev= 30
  4766.5 1455.46  4795.6 1449.41  4822.1 1444.93  4863.9 1430.39  4879.5 1427.37
  4912.1 1415.24  4917.4 1415.32  4935.9 1407.57  4944.8 1403.12  4989.5 1403.61
  5002.5 1401.69  5003.0 1401.19  5013.2 1401.69  5035.6 1402.38  5052.2 1411.83
  5063.6 1413.90  5096.6 1423.01  5163.2 1431.75  5179.7 1435.10  5213.4 1444.62
  5268.6 1451.33  5274.2 1453.35  5313.0 1456.70  5318.6 1458.64  5335.2 1458.95
  5340.8 1461.25  5357.4 1461.01  5363.0 1462.84  5379.6 1462.21  5391.7 1463.47
#Mann=6,-1,0
  4766.5    0.07       0  4795.6    0.16       0  4935.9    0.07       0
  5002.5    0.07       0  5013.2    0.07       0  5063.6   0.035       0
Bank Sta=5002.5,5013.2
Exp/Cntr=0.3,0.1

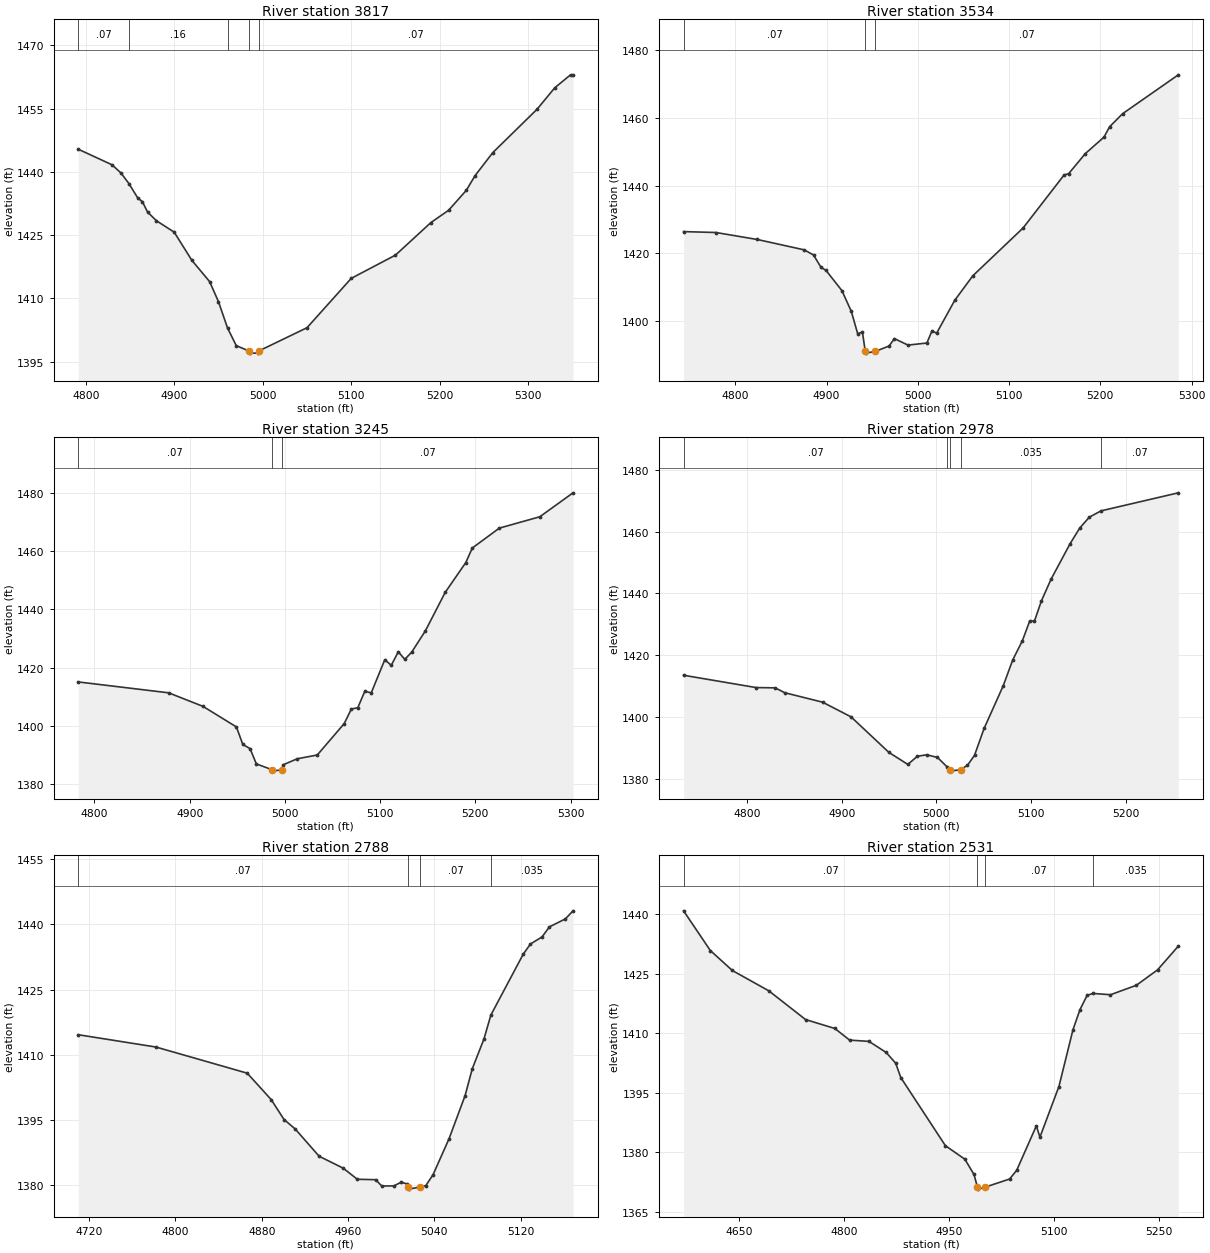
Type RM Length L Ch R = 1,3817,283,283,283
BEGIN DESCRIPTION:
Mapping XS e2f40986
END DESCRIPTION:
XS GIS Cut Line= 3
      1688264.75      7043079.84      1688250.65      7043291.44
      1688251.73      7043638.67
#Sta/Elev= 30
  4791.4 1445.36  4829.6 1441.67  4839.7 1439.72  4848.6 1437.23  4858.8 1433.75
  4863.8 1432.96  4869.7 1430.47  4879.8 1428.40  4899.8 1425.71  4919.8 1419.02
  4939.9 1413.97  4949.9 1409.21  4960.1 1403.00  4970.0 1398.79  4984.5 1397.52
  4985.0 1397.02  4994.9 1397.02  4995.4 1397.52  5050.0 1403.05  5100.0 1414.75
  5150.0 1420.26  5190.0 1427.97  5210.0 1430.88  5230.0 1435.60  5240.0 1439.11
  5260.0 1444.56  5310.0 1454.83  5330.0 1459.92  5347.9 1463.00  5350.7 1463.00
#Mann=5,-1,0
  4791.4    0.07       0  4848.6    0.16       0  4960.1    0.07       0
  4984.5    0.07       0  4995.4    0.07       0
Bank Sta=4984.5,4995.4
Exp/Cntr=0.3,0.1

Type RM Length L Ch R = 1,3534,289,289,289
BEGIN DESCRIPTION:
Mapping XS e071acb4
END DESCRIPTION:
XS GIS Cut Line= 3
      1688049.55      7043090.34      1687982.27      7043343.16
      1687924.76      7043617.69
#Sta/Elev= 30
  4743.3 1426.45  4778.8 1426.18  4824.1 1424.12  4875.4 1421.07  4885.7 1419.55
  4894.0 1415.86  4899.2 1415.06  4916.8 1409.04  4927.1 1402.91  4934.1 1396.31
  4939.3 1396.80  4942.4 1391.09  4942.9 1390.59  4953.3 1391.09  4968.5 1392.69
  4974.3 1394.88  4989.2 1392.96  5009.9 1393.57  5015.5 1397.15  5020.6 1396.48
  5040.5 1406.20  5060.3 1413.43  5115.3 1427.51  5160.2 1443.14  5165.3 1443.56
  5183.5 1449.46  5204.0 1454.34  5210.1 1457.39  5224.4 1461.25  5285.4 1472.71
#Mann=3,-1,0
  4743.3    0.07       0  4942.4    0.07       0  4953.3    0.07       0
Bank Sta=4942.4,4953.3
Exp/Cntr=0.3,0.1

Type RM Length L Ch R = 1,3245,267,267,267
BEGIN DESCRIPTION:
Chimney Creek 1192 7.0
END DESCRIPTION:
XS GIS Cut Line= 3
      1687874.90      7043143.61      1687710.93      7043285.75
      1687507.01      7043509.33
#Sta/Elev= 30
  4783.0 1415.12  4877.9 1411.39  4914.0 1406.74  4949.1 1399.69  4955.8 1393.67
  4963.4 1392.27  4970.0 1387.02  4986.4 1385.04  4986.9 1384.54  4997.3 1385.04
  4997.9 1386.67  5013.0 1388.78  5034.0 1390.07  5062.3 1400.85  5069.8 1405.85
  5076.5 1406.25  5083.9 1411.90  5090.7 1411.40  5104.9 1422.74  5111.7 1420.82
  5119.1 1425.46  5125.9 1422.86  5133.3 1425.40  5147.5 1432.62  5168.4 1445.86
  5190.0 1456.06  5196.8 1461.04  5225.2 1467.86  5267.7 1471.75  5302.6 1479.96
#Mann=3,-1,0
  4783.0    0.07       0  4986.4    0.07       0  4997.3    0.07       0
Bank Sta=4986.4,4997.3
Exp/Cntr=0.3,0.1

Type RM Length L Ch R = 1,2978,190,190,190
BEGIN DESCRIPTION:
Mapping XS acfee61c
END DESCRIPTION:
XS GIS Cut Line= 3
      1687821.73      7043114.33      1687553.70      7043108.90
      1687301.92      7043144.72
#Sta/Elev= 30
  4733.0 1413.55  4809.7 1409.56  4829.7 1409.48  4839.7 1407.91  4879.8 1404.84
  4909.8 1400.10  4949.8 1388.60  4969.8 1384.71  4979.8 1387.34  4989.8 1387.83
  5001.1 1386.97  5011.3 1383.91  5014.5 1383.04  5015.0 1382.54  5025.5 1383.04
  5032.7 1384.41  5040.2 1387.64  5050.3 1396.33  5070.5 1410.12  5080.6 1418.53
  5090.7 1424.67  5098.5 1431.11  5103.5 1431.06  5110.9 1437.65  5121.0 1444.60
  5141.2 1456.13  5151.3 1461.15  5161.4 1464.67  5173.7 1466.71  5255.4 1472.55
#Mann=5,-1,0
  4733.0    0.07       0  5011.3   0.035       0  5014.5    0.07       0
  5025.5   0.035       0  5173.7    0.07       0
Bank Sta=5014.5,5025.5
Exp/Cntr=0.3,0.1

Type RM Length L Ch R = 1,2788,257,257,257
BEGIN DESCRIPTION:
Chimney Creek 1192 6.0
END DESCRIPTION:
XS GIS Cut Line= 3
      1687866.01      7043063.56      1687605.00      7042938.00
      1687448.38      7042875.41
#Sta/Elev= 30
  4710.1 1414.61  4782.0 1411.78  4866.6 1405.76  4888.8 1399.68  4900.7 1395.09
  4911.0 1392.93  4933.2 1386.64  4955.4 1383.91  4968.6 1381.34  4985.6 1381.24
  4991.2 1379.79  5002.4 1379.81  5009.2 1380.66  5014.6 1380.27  5015.8 1379.57
  5016.3 1379.07  5026.8 1379.57  5032.0 1379.87  5038.8 1382.42  5053.6 1390.70
  5068.4 1400.59  5075.1 1406.80  5085.9 1413.63  5092.3 1419.14  5122.3 1433.17
  5129.0 1435.50  5139.7 1437.12  5146.5 1439.44  5161.3 1441.27  5168.4 1443.13
#Mann=4,-1,0
  4710.1    0.07       0  5015.8    0.07       0  5026.8    0.07       0
  5092.3   0.035       0
Bank Sta=5015.8,5026.8
Exp/Cntr=0.3,0.1

Type RM Length L Ch R = 1,2531,214,214,214
BEGIN DESCRIPTION:
Mapping XS 8c7ce0c9
END DESCRIPTION:
XS GIS Cut Line= 3
      1688161.57      7042860.43      1687750.10      7042735.42
      1687475.40      7042762.76
#Sta/Elev= 30
  4571.3 1440.83  4609.5 1430.84  4640.9 1425.81  4693.1 1420.68  4745.4 1413.46
  4787.2 1411.22  4808.3 1408.29  4835.9 1407.97  4860.4 1405.19  4874.0 1402.49
  4881.3 1398.87  4945.0 1381.71  4972.7 1378.32  4985.8 1374.47  4990.7 1371.28
  4991.2 1370.78  5001.7 1371.28  5036.6 1373.32  5046.7 1375.51  5074.8 1386.71
  5079.9 1383.86  5107.0 1396.61  5127.1 1410.92  5137.1 1415.98  5147.2 1419.54
  5155.5 1420.04  5180.6 1419.71  5217.5 1422.09  5247.7 1425.96  5277.4 1431.94
#Mann=4,-1,0
  4571.3    0.07       0  4990.7    0.07       0  5001.7    0.07       0
  5155.5   0.035       0
Bank Sta=4990.7,5001.7
Exp/Cntr=0.3,0.1

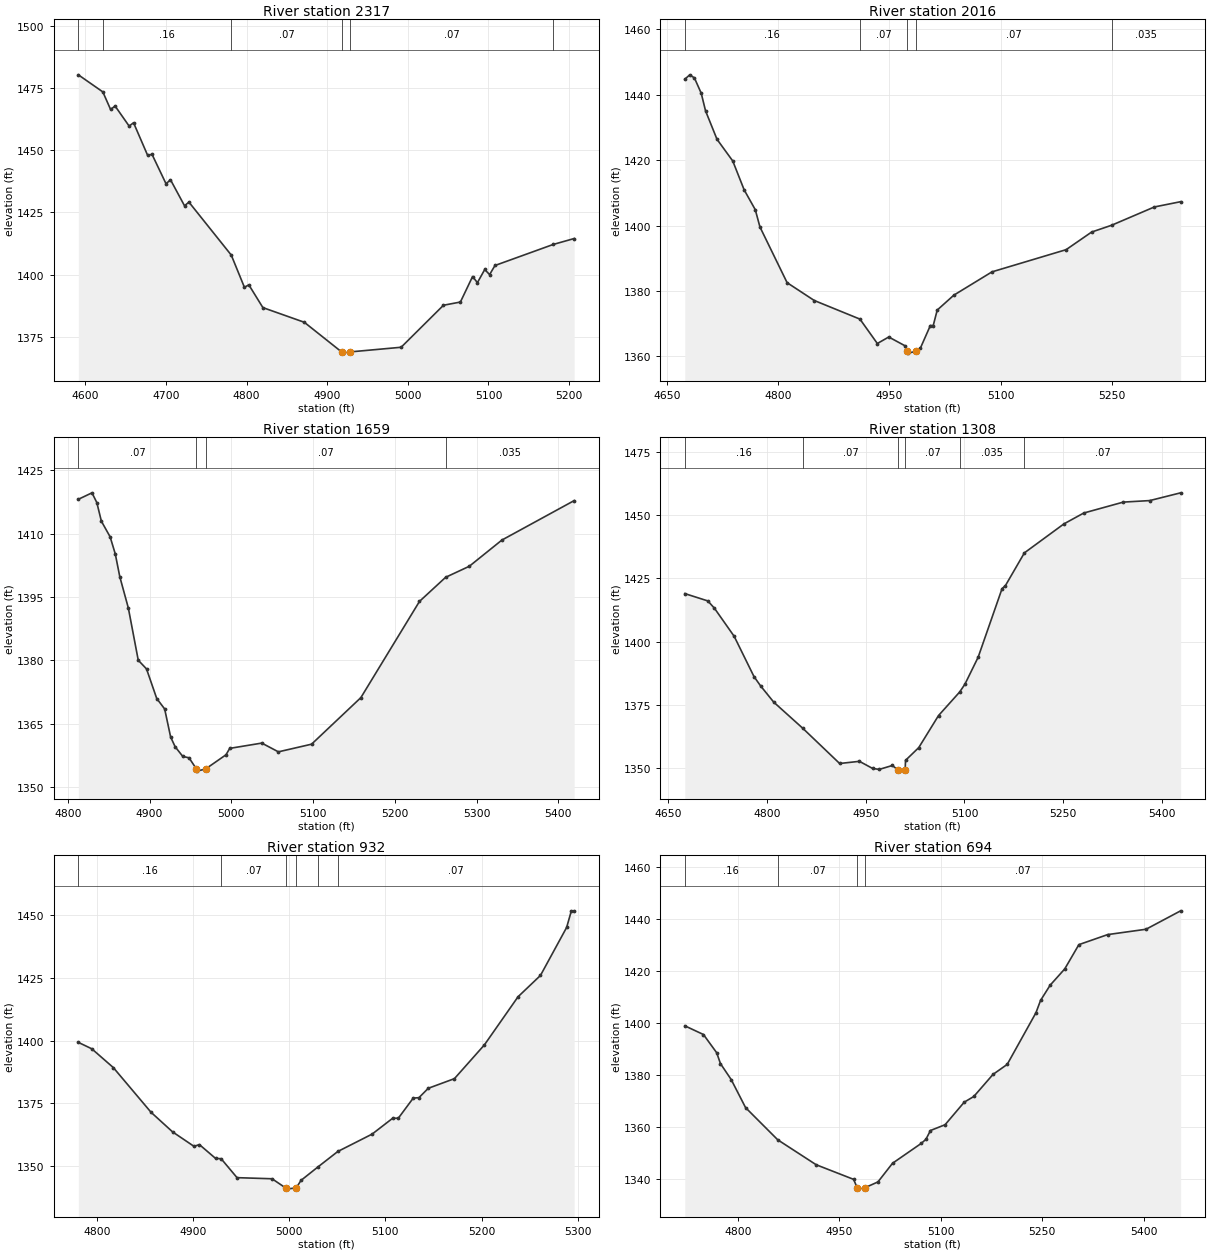
Type RM Length L Ch R = 1,2317,301,301,301
BEGIN DESCRIPTION:
Chimney Creek 1192 5.0
END DESCRIPTION:
XS GIS Cut Line= 3
      1688176.31      7042366.17      1687805.00      7042538.00
      1687632.88      7042650.92
#Sta/Elev= 30
  4591.3 1480.34  4621.7 1473.47  4631.3 1466.41  4636.9 1467.79  4654.3 1459.73
  4659.8 1461.06  4677.2 1448.00  4682.7 1448.35  4700.1 1436.51  4705.6 1438.15
  4723.0 1427.68  4728.5 1429.13  4781.0 1407.83  4797.3 1394.88  4802.8 1395.86
  4820.2 1386.71  4871.6 1380.81  4917.8 1368.90  4918.3 1368.40  4928.8 1368.90
  4991.7 1370.76  5044.2 1387.66  5065.2 1388.95  5080.3 1399.21  5086.3 1396.74
  5095.4 1402.04  5101.4 1399.98  5108.1 1403.65  5180.5 1412.13  5206.3 1414.49
#Mann=6,-1,0
  4591.3    0.07       0  4621.7    0.16       0  4781.0    0.07       0
  4917.8    0.07       0  4928.8    0.07       0  5180.5   0.035       0
Bank Sta=4917.8,4928.8
Exp/Cntr=0.3,0.1

Type RM Length L Ch R = 1,2016,357,357,357
BEGIN DESCRIPTION:
Mapping XS 20cbed86
END DESCRIPTION:
XS GIS Cut Line= 3
      1688046.12      7042079.70      1687763.12      7042253.32
      1687615.54      7042557.16
#Sta/Elev= 30
  4673.5 1444.75  4680.2 1446.09  4686.5 1445.14  4695.7 1440.46  4701.5 1435.10
  4717.0 1426.38  4738.3 1419.74  4753.7 1410.91  4768.7 1404.86  4775.0 1399.58
  4811.7 1382.54  4848.4 1377.09  4910.1 1371.40  4933.6 1363.94  4949.0 1365.93
  4970.3 1363.33  4974.3 1361.50  4974.8 1361.00  4985.3 1361.50  4991.6 1362.45
  5005.2 1369.43  5009.1 1369.43  5014.5 1374.17  5037.0 1378.73  5088.5 1385.85
  5188.6 1392.63  5223.1 1398.02  5250.0 1400.09  5307.8 1405.69  5343.3 1407.30
#Mann=5,-1,0
  4673.5    0.16       0  4910.1    0.07       0  4974.3    0.07       0
  4985.3    0.07       0  5250.0   0.035       0
Bank Sta=4974.3,4985.3
Exp/Cntr=0.3,0.1

Type RM Length L Ch R = 1,1659,351,351,351
BEGIN DESCRIPTION:
Chimney Creek 1192 4.0
END DESCRIPTION:
XS GIS Cut Line= 3
      1687429.99      7042062.97      1687511.65      7042231.31
      1687584.64      7042644.31
#Sta/Elev= 30
  4812.9 1418.09  4829.6 1419.62  4835.5 1417.32  4841.1 1412.91  4851.8 1409.21
  4858.1 1405.17  4863.6 1399.80  4874.1 1392.36  4886.2 1380.04  4896.3 1377.99
  4908.8 1370.99  4918.5 1368.52  4925.8 1361.89  4931.3 1359.59  4940.7 1357.29
  4948.3 1356.97  4957.4 1354.32  4957.9 1353.82  4968.5 1354.32  4993.5 1357.68
  4998.1 1359.20  5037.3 1360.45  5057.6 1358.38  5098.2 1360.19  5158.5 1371.20
  5230.2 1393.95  5262.2 1399.65  5291.1 1402.25  5331.0 1408.45  5419.4 1417.78
#Mann=4,-1,0
  4812.9    0.07       0  4957.4    0.07       0  4968.5    0.07       0
  5262.2   0.035       0
Bank Sta=4957.4,4968.5
Exp/Cntr=0.3,0.1

Type RM Length L Ch R = 1,1308,376,376,376
BEGIN DESCRIPTION:
Chimney Creek 1192 3.0
END DESCRIPTION:
XS GIS Cut Line= 3
      1687280.00      7042163.04      1687289.79      7042487.49
      1687317.41      7042914.80
#Sta/Elev= 30
  4675.4 1419.02  4710.4 1416.11  4720.4 1413.22  4750.4 1402.09  4780.4 1386.19
  4790.4 1382.50  4810.4 1376.05  4854.5 1365.70  4910.5 1351.75  4940.5 1352.61
  4960.5 1349.80  4970.5 1349.41  4990.5 1350.96  4998.9 1349.23  4999.4 1348.73
  5010.0 1349.23  5010.5 1352.99  5030.6 1358.04  5060.6 1370.72  5092.8 1380.08
  5100.7 1383.15  5120.8 1393.83  5157.1 1420.99  5162.1 1422.14  5191.0 1435.14
  5251.0 1446.61  5281.1 1450.91  5341.2 1455.24  5381.3 1455.84  5428.2 1458.91
#Mann=6,-1,0
  4675.4    0.16       0  4854.5    0.07       0  4998.9    0.07       0
  5010.0    0.07       0  5092.8   0.035       0  5191.0    0.07       0
Bank Sta=4998.9,5010
Exp/Cntr=0.3,0.1

Type RM Length L Ch R = 1,932,238,238,238
BEGIN DESCRIPTION:
Chimney Creek 1192 2.0
END DESCRIPTION:
XS GIS Cut Line= 3
      1687055.01      7042237.97      1686955.00      7042438.00
      1686804.99      7042688.01
#Sta/Elev= 30
  4780.9 1399.32  4794.9 1396.75  4817.3 1389.25  4856.4 1371.47  4878.8 1363.65
  4901.1 1357.87  4906.7 1358.57  4923.5 1353.07  4929.3 1352.94  4945.8 1345.39
  4982.2 1344.95  4996.2 1341.32  4996.7 1340.82  5007.3 1341.32  5012.3 1344.31
  5030.1 1349.73  5050.5 1355.82  5086.2 1362.76  5107.5 1369.07  5113.4 1369.09
  5128.9 1377.11  5134.8 1377.27  5144.5 1381.01  5171.7 1384.86  5202.8 1398.30
  5237.8 1417.50  5261.1 1426.00  5288.3 1445.14  5293.2 1451.75  5296.1 1451.75
#Mann=6,-1,0
  4780.9    0.16       0  4929.3    0.07       0  4996.2    0.07       0
  5007.3    0.07       0  5030.1   0.035       0  5050.5    0.07       0
Bank Sta=4996.2,5007.3
Exp/Cntr=0.3,0.1

Type RM Length L Ch R = 1,694,444,444,444
BEGIN DESCRIPTION:
Mapping XS 9a11d674
END DESCRIPTION:
XS GIS Cut Line= 3
      1687029.33      7042204.71      1686765.43      7042301.94
      1686432.12      7042607.48
#Sta/Elev= 30
  4721.3 1398.81  4748.9 1395.46  4768.5 1388.45  4774.0 1384.31  4789.9 1378.17
  4811.2 1367.38  4858.8 1355.01  4915.6 1345.44  4971.0 1339.82  4976.3 1336.57
  4976.8 1336.07  4987.4 1336.57  5007.0 1338.84  5028.6 1346.01  5070.9 1353.61
  5077.9 1355.19  5084.7 1358.59  5106.3 1360.81  5134.6 1369.47  5148.8 1371.66
  5177.2 1380.14  5198.2 1383.99  5240.7 1403.82  5247.5 1408.55  5261.7 1414.41
  5283.3 1420.67  5304.2 1429.99  5346.8 1433.85  5403.5 1435.90  5454.7 1442.98
#Mann=4,-1,0
  4721.3    0.16       0  4858.8    0.07       0  4976.3    0.07       0
  4987.4    0.07       0
Bank Sta=4976.3,4987.4
Exp/Cntr=0.3,0.1

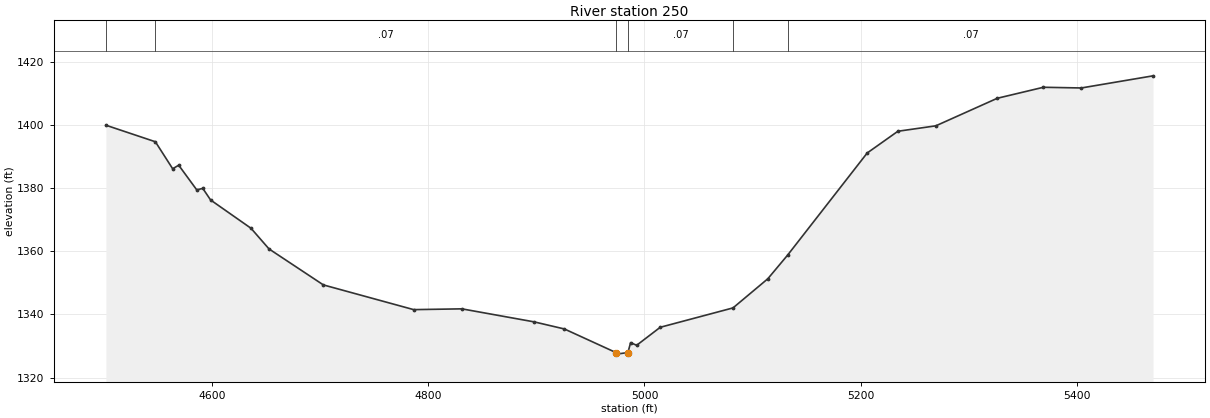
Type RM Length L Ch R = 1,250,0,0,0
BEGIN DESCRIPTION:
Chimney Creek 1192 1.0
END DESCRIPTION:
XS GIS Cut Line= 3
      1687001.56      7042152.64      1686556.38      7041928.33
      1686244.60      7042281.10
#Sta/Elev= 30
  4501.5 1400.03  4547.3 1394.78  4563.3 1386.22  4568.9 1387.34  4585.6 1379.52
  4591.2 1379.99  4598.4 1376.32  4635.8 1367.35  4652.5 1360.79  4702.8 1349.38
  4786.4 1341.54  4831.0 1341.79  4897.9 1337.66  4925.9 1335.41  4973.6 1327.93
  4974.1 1327.43  4984.7 1327.93  4987.2 1331.07  4992.8 1330.23  5014.6 1335.94
  5082.0 1342.09  5114.2 1351.33  5132.5 1358.82  5206.2 1391.22  5234.6 1398.11
  5269.7 1399.83  5326.6 1408.57  5369.3 1412.06  5404.4 1411.84  5470.8 1415.69
#Mann=6,-1,0
  4501.5    0.16       0  4547.3    0.07       0  4973.6    0.07       0
  4984.7    0.07       0  5082.0   0.035       0  5132.5    0.07       0
Bank Sta=4973.6,4984.7
Exp/Cntr=0.3,0.1

Chan Stop Cuts=-1