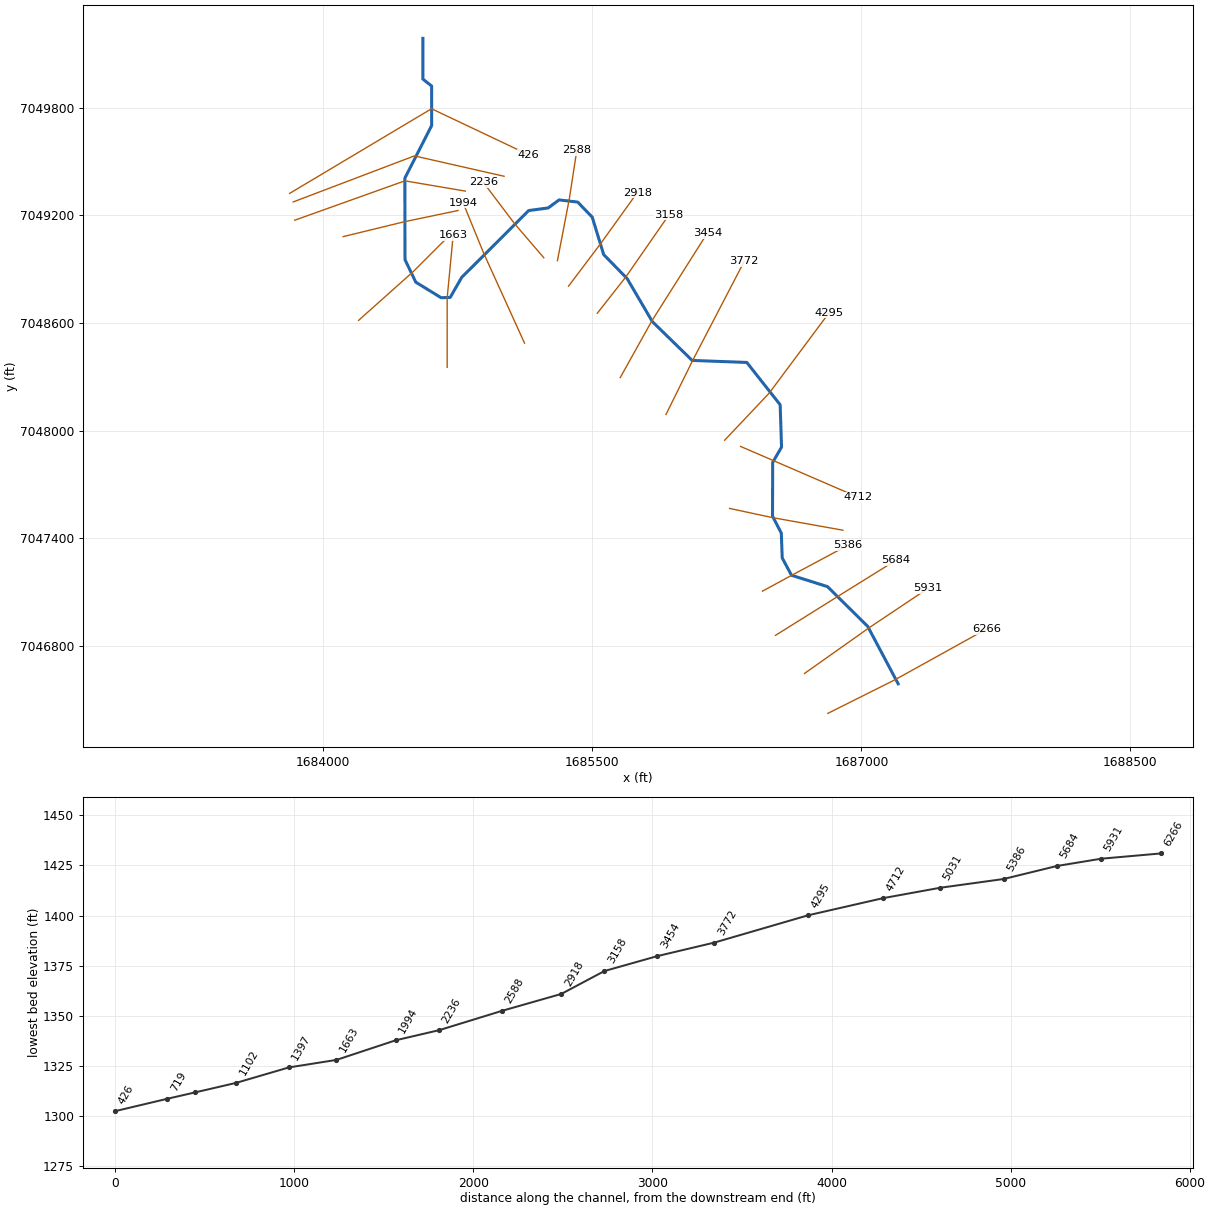
--- Chimney Creek 1193.prj (project) ---

Proj Title=Chimney Creek 1193 Base Level Engineering
Current Plan=p01
Default Exp/Contr=0.3,0.1
English Units
Geom File=g01
Flow File=f01
Plan File=p01
BEGIN DESCRIPTION:
Chimney Creek 1193
END DESCRIPTION:

--- Chimney Creek 1193.p01 (plan) ---

Plan Title=Multiple Run
Short Identifier=Multiple
Geom File=g01
Flow File=f01
Subcritical Flow
K Sum by GR= 0
Std Step Tol= 0.01
Critical Tol= 0.01
Num of Std Step Trials= 20
Max Error Tol= 0.3
Flow Tol Ratio= 0.001
Split Flow NTrial= 30
Split Flow Tol= 0.02
Split Flow Ratio= 0.02
Log Output Level= 0
Friction Slope Method= 1
Unsteady Friction Slope Method= 2
Unsteady Bridges Friction Slope Method= 1
Parabolic Critical Depth
Global Vel Dist=  1 , 1 , 1
Global Log Level= 0
CheckData=True
Encroach Param= -1, 0, 0, 0
BEGIN DESCRIPTION:
Multiple Run
END DESCRIPTION:

--- Chimney Creek 1193.f01 (steady flow) ---

Flow Title=Multiple
Number of Profiles=7
Profile Names=10-year,25-year,50-year,1pct_min,100-year,1pct_plu,500-year
River Rch & RM= Chimney Creek 11,Reach-1,6266
     267     370     455     279     557    1112     846
River Rch & RM= Chimney Creek 11,Reach-1,4712
     441     632     796     500     997    1990    1583
Boundary for River Rch & Prof#=Chimney Creek 11,Reach-1,1
Up Type=0
Dn Type=3
Dn Slope=0.005
Boundary for River Rch & Prof#=Chimney Creek 11,Reach-1,2
Up Type=0
Dn Type=3
Dn Slope=0.005
Boundary for River Rch & Prof#=Chimney Creek 11,Reach-1,3
Up Type=0
Dn Type=3
Dn Slope=0.005
Boundary for River Rch & Prof#=Chimney Creek 11,Reach-1,4
Up Type=0
Dn Type=3
Dn Slope=0.005
Boundary for River Rch & Prof#=Chimney Creek 11,Reach-1,5
Up Type=0
Dn Type=3
Dn Slope=0.005
Boundary for River Rch & Prof#=Chimney Creek 11,Reach-1,6
Up Type=0
Dn Type=3
Dn Slope=0.005
Boundary for River Rch & Prof#=Chimney Creek 11,Reach-1,7
Up Type=0
Dn Type=3
Dn Slope=0.005

--- Chimney Creek 1193.g01 (geometry) ---

Geom Title=Existing Conditions

River Reach=Chimney Creek 11,Reach-1
Reach XY= 30
      1687205.00      7046588.00      1687035.22      7046908.09
      1686811.06      7047129.86      1686610.44      7047193.25
      1686558.74      7047289.52      1686553.61      7047428.33
      1686504.57      7047522.82      1686505.52      7047822.78
      1686554.93      7047908.03      1686547.17      7048144.19
      1686361.21      7048380.20      1686056.46      7048391.54
      1685834.62      7048607.84      1685694.22      7048847.68
      1685563.14      7048981.94      1685499.48      7049190.44
      1685418.33      7049274.68      1685314.71      7049286.74
      1685253.40      7049241.86      1685145.21      7049227.48
      1684771.66      7048854.66      1684707.55      7048742.98
      1684656.76      7048741.30      1684515.63      7048828.00
      1684455.51      7048953.21      1684454.64      7049408.15
      1684604.33      7049701.91      1684604.04      7049922.04
      1684555.04      7049960.77      1684555.00      7050188.00

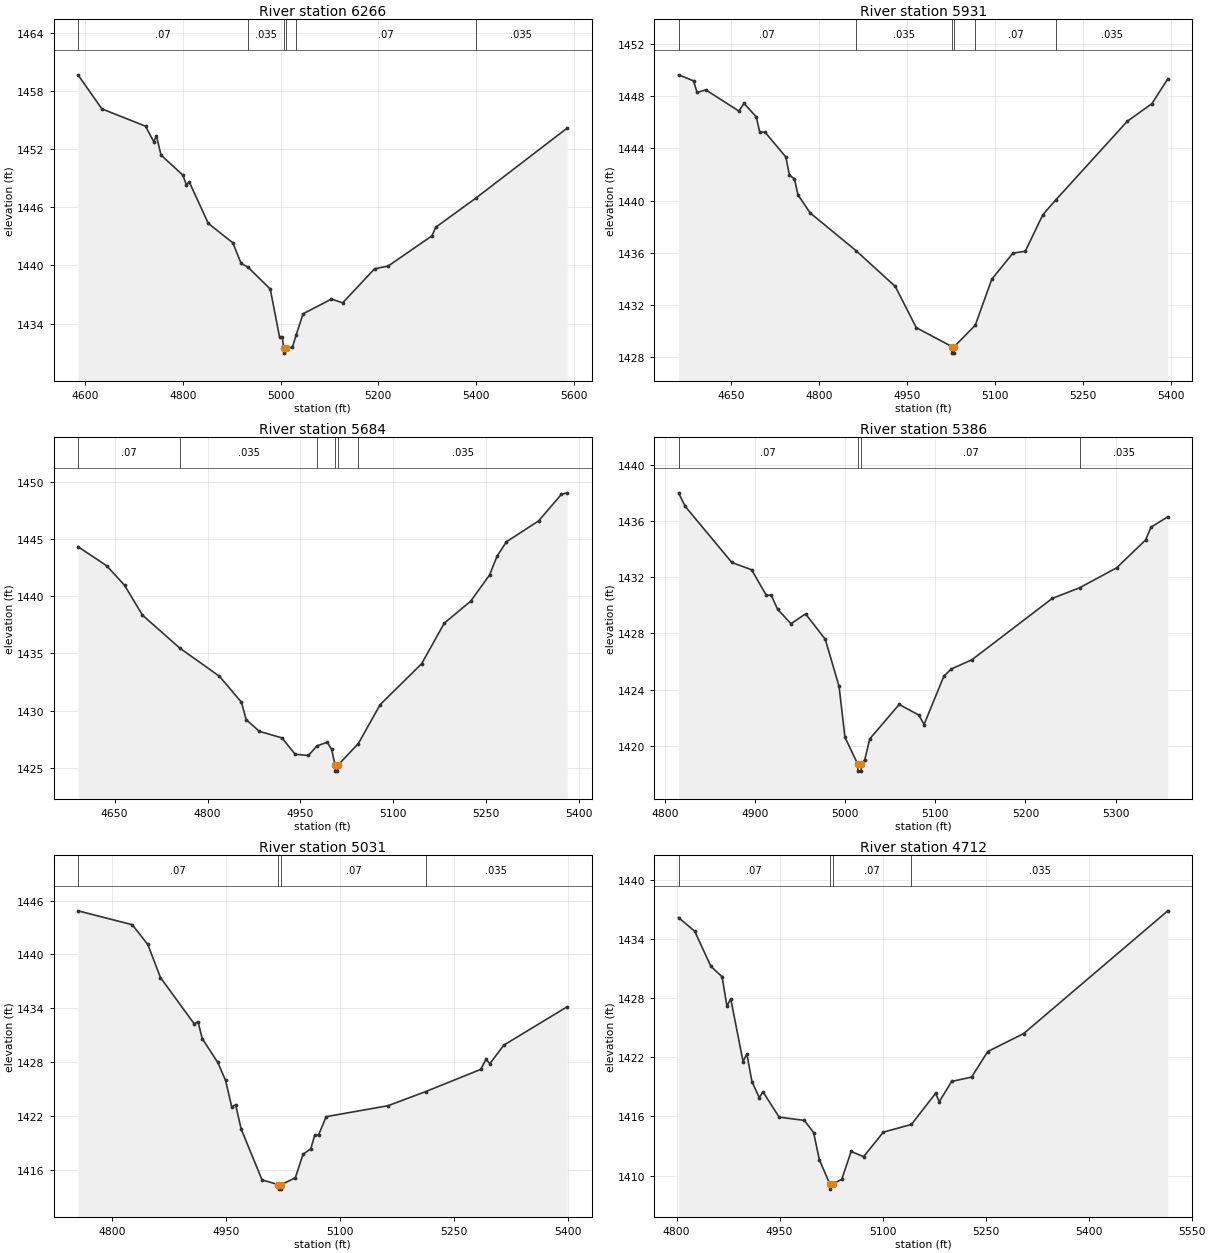
Type RM Length L Ch R = 1,6266,335,335,335
BEGIN DESCRIPTION:
Chimney Creek 1193 13.0
END DESCRIPTION:
XS GIS Cut Line= 3
      1686813.01      7046422.84      1687183.78      7046608.39
      1687697.11      7046892.88
#Sta/Elev= 30
  4585.4 1459.67  4634.2 1456.16  4723.6 1454.37  4740.4 1452.78  4746.0 1453.36
  4755.4 1451.39  4800.1 1449.32  4807.4 1448.29  4813.0 1448.63  4852.1 1444.34
  4902.4 1442.33  4919.2 1440.22  4933.8 1439.80  4979.0 1437.56  4997.9 1432.63
  5003.6 1432.63  5006.3 1431.45  5006.6 1430.95  5010.3 1431.45  5024.3 1431.56
  5031.8 1432.80  5046.1 1435.01  5104.3 1436.53  5127.2 1436.14  5192.6 1439.66
  5220.1 1439.93  5310.1 1443.06  5317.4 1443.93  5399.1 1446.92  5586.9 1454.18
#Mann=6,-1,0
  4585.4    0.07       0  4933.8   0.035       0  5006.3   0.035       0
  5010.3   0.035       0  5031.8    0.07       0  5399.1   0.035       0
Bank Sta=5006.3,5010.3
Exp/Cntr=0.3,0.1

Type RM Length L Ch R = 1,5931,247,247,247
BEGIN DESCRIPTION:
Mapping XS 1e07f874
END DESCRIPTION:
XS GIS Cut Line= 3
      1686682.98      7046645.47      1687043.23      7046900.47
      1687370.50      7047119.37
#Sta/Elev= 30
  4559.6 1449.64  4585.2 1449.18  4591.3 1448.29  4606.1 1448.49  4662.7 1446.86
  4671.4 1447.45  4692.3 1446.42  4698.4 1445.23  4707.0 1445.26  4742.7 1443.35
  4748.9 1441.96  4757.5 1441.66  4763.6 1440.43  4784.5 1439.05  4862.7 1436.16
  4929.6 1433.42  4965.5 1430.26  5026.3 1428.81  5026.6 1428.31  5030.1 1428.31
  5030.3 1428.81  5066.1 1430.45  5094.4 1433.98  5130.4 1435.97  5151.5 1436.12
  5181.5 1438.92  5204.1 1440.08  5325.6 1446.08  5367.6 1447.43  5394.7 1449.33
#Mann=6,-1,0
  4559.6    0.07       0  4862.7   0.035       0  5026.3   0.035       0
  5030.3   0.035       0  5066.1    0.07       0  5204.1   0.035       0
Bank Sta=5026.3,5030.3
Exp/Cntr=0.3,0.1

Type RM Length L Ch R = 1,5684,298,298,298
BEGIN DESCRIPTION:
Mapping XS 91ddf575
END DESCRIPTION:
XS GIS Cut Line= 3
      1686521.29      7046858.14      1686868.53      7047075.17
      1687191.46      7047276.05
#Sta/Elev= 30
  4590.9 1444.36  4637.2 1442.69  4666.0 1440.98  4695.0 1438.36  4755.5 1435.46
  4819.3 1433.00  4854.7 1430.73  4862.4 1429.20  4883.6 1428.18  4920.2 1427.60
  4941.4 1426.17  4962.7 1426.06  4976.7 1426.90  4993.3 1427.22  5000.4 1426.59
  5006.0 1425.19  5006.3 1424.69  5009.8 1424.69  5010.0 1425.19  5043.4 1427.10
  5078.7 1430.52  5145.6 1434.10  5182.2 1437.66  5224.7 1439.58  5255.3 1441.88
  5267.2 1443.51  5282.5 1444.79  5334.5 1446.62  5371.1 1448.94  5380.7 1449.08
#Mann=6,-1,0
  4590.9    0.07       0  4755.5   0.035       0  4976.7    0.07       0
  5006.0    0.07       0  5010.0    0.07       0  5043.4   0.035       0
Bank Sta=5006,5010
Exp/Cntr=0.3,0.1

Type RM Length L Ch R = 1,5386,355,355,355
BEGIN DESCRIPTION:
Mapping XS 2f4ca90e
END DESCRIPTION:
XS GIS Cut Line= 3
      1686448.41      7047104.49      1686611.63      7047193.05
      1686926.75      7047361.46
#Sta/Elev= 30
  4814.9 1438.01  4822.4 1437.04  4874.1 1433.05  4896.0 1432.53  4912.2 1430.73
  4917.9 1430.71  4924.8 1429.73  4939.7 1428.69  4955.9 1429.39  4977.8 1427.58
  4993.1 1424.22  4999.6 1420.61  5013.8 1418.69  5014.0 1418.19  5017.5 1418.19
  5017.8 1418.69  5021.6 1419.00  5027.2 1420.49  5059.8 1422.94  5081.7 1422.18
  5087.4 1421.51  5109.4 1424.95  5117.8 1425.47  5140.5 1426.12  5229.7 1430.49
  5260.1 1431.25  5301.2 1432.67  5333.2 1434.65  5339.4 1435.57  5357.9 1436.30
#Mann=4,-1,0
  4814.9    0.07       0  5013.8    0.07       0  5017.8    0.07       0
  5260.1   0.035       0
Bank Sta=5013.8,5017.8
Exp/Cntr=0.3,0.1

Type RM Length L Ch R = 1,5031,319,319,319
BEGIN DESCRIPTION:
Mapping XS 1a4b367a
END DESCRIPTION:
XS GIS Cut Line= 3
      1686265.20      7047566.05      1686503.91      7047514.84
      1686897.13      7047444.52
#Sta/Elev= 30
  4755.0 1444.85  4826.4 1443.30  4846.8 1441.10  4863.5 1437.41  4907.8 1432.26
  4912.9 1432.46  4918.4 1430.61  4938.9 1427.94  4949.1 1425.95  4957.2 1423.00
  4962.3 1423.23  4969.6 1420.53  4997.1 1414.85  5018.6 1414.32  5018.8 1413.82
  5022.3 1413.82  5022.6 1414.32  5040.9 1415.09  5051.0 1417.71  5061.2 1418.31
  5066.3 1419.81  5071.4 1419.85  5081.5 1421.90  5162.8 1423.12  5212.2 1424.69
  5284.7 1427.17  5291.7 1428.28  5296.8 1427.81  5315.2 1429.88  5398.6 1434.16
#Mann=4,-1,0
  4755.0    0.07       0  5018.6    0.07       0  5022.6    0.07       0
  5212.2   0.035       0
Bank Sta=5018.6,5022.6
Exp/Cntr=0.3,0.1

Type RM Length L Ch R = 1,4712,417,417,417
BEGIN DESCRIPTION:
Mapping XS 0c9dffcc
END DESCRIPTION:
XS GIS Cut Line= 3
      1686326.84      7047911.70      1686507.38      7047833.59
      1686980.65      7047629.02
#Sta/Elev= 30
  4802.9 1436.17  4826.5 1434.78  4850.0 1431.22  4866.3 1430.17  4873.4 1427.19
  4878.9 1427.93  4896.9 1421.57  4902.4 1422.34  4909.8 1419.54  4920.4 1417.91
  4925.9 1418.50  4949.4 1415.93  4986.1 1415.60  4999.6 1414.37  5007.9 1411.62
  5023.3 1409.13  5023.5 1408.63  5027.3 1409.13  5040.6 1409.63  5054.2 1412.45
  5072.3 1411.92  5101.2 1414.41  5142.0 1415.19  5177.1 1418.34  5182.6 1417.50
  5200.6 1419.55  5229.6 1419.99  5253.1 1422.58  5305.5 1424.41  5515.2 1436.85
#Mann=4,-1,0
  4802.9    0.07       0  5023.3    0.07       0  5027.3    0.07       0
  5142.0   0.035       0
Bank Sta=5023.3,5027.3
Exp/Cntr=0.3,0.1

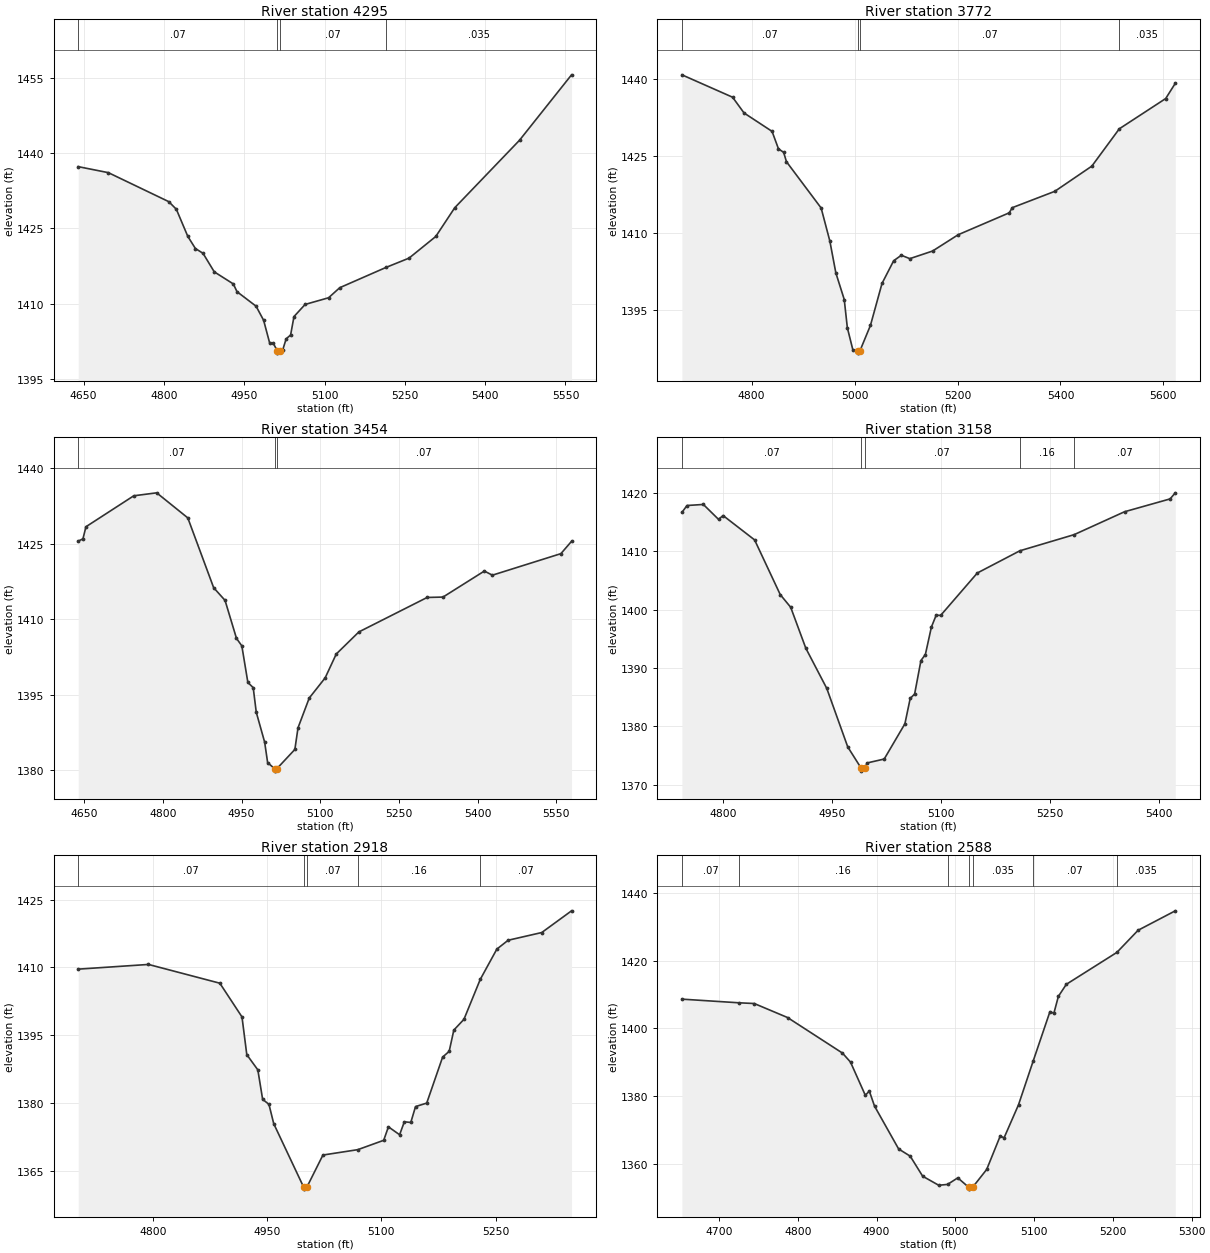
Type RM Length L Ch R = 1,4295,523,523,523
BEGIN DESCRIPTION:
Mapping XS 6fb714c0
END DESCRIPTION:
XS GIS Cut Line= 3
      1686237.49      7047946.18      1686486.18      7048209.20
      1686820.38      7048657.83
#Sta/Elev= 30
  4640.0 1437.31  4696.3 1436.11  4809.1 1430.33  4823.3 1428.81  4844.7 1423.40
  4858.9 1420.98  4873.1 1420.03  4894.1 1416.33  4929.7 1413.92  4936.6 1412.37
  4972.2 1409.48  4986.3 1406.67  4997.7 1402.09  5004.3 1402.09  5011.6 1400.62
  5011.9 1400.12  5016.0 1400.62  5022.1 1400.81  5028.4 1402.97  5036.7 1403.74
  5043.0 1407.41  5063.8 1409.83  5107.6 1411.16  5128.5 1413.17  5215.3 1417.23
  5257.8 1419.06  5307.8 1423.38  5343.3 1429.12  5464.2 1442.57  5561.4 1455.62
#Mann=4,-1,0
  4640.0    0.07       0  5011.6    0.07       0  5016.0    0.07       0
  5215.3   0.035       0
Bank Sta=5011.6,5016
Exp/Cntr=0.3,0.1

Type RM Length L Ch R = 1,3772,318,318,318
BEGIN DESCRIPTION:
Mapping XS e9f8f678
END DESCRIPTION:
XS GIS Cut Line= 3
      1685910.60      7048089.80      1686060.32      7048393.14
      1686346.55      7048943.48
#Sta/Elev= 30
  4664.5 1440.73  4762.9 1436.37  4785.2 1433.30  4839.6 1429.72  4852.1 1426.31
  4862.1 1425.64  4867.6 1423.81  4935.0 1414.79  4951.9 1408.36  4963.6 1402.14
  4979.9 1396.97  4985.9 1391.48  4996.8 1387.10  5006.1 1387.03  5006.4 1386.53
  5010.6 1387.03  5030.8 1391.93  5053.3 1400.11  5075.9 1404.52  5090.8 1405.59
  5107.3 1404.93  5151.5 1406.41  5201.3 1409.59  5300.6 1413.86  5306.2 1414.85
  5389.0 1418.04  5461.0 1422.95  5514.4 1430.22  5604.5 1436.11  5623.1 1439.07
#Mann=4,-1,0
  4664.5    0.07       0  5006.1    0.07       0  5010.6    0.07       0
  5514.4   0.035       0
Bank Sta=5006.1,5010.6
Exp/Cntr=0.3,0.1

Type RM Length L Ch R = 1,3454,296,296,296
BEGIN DESCRIPTION:
Mapping XS dbf71666
END DESCRIPTION:
XS GIS Cut Line= 3
      1685655.38      7048295.50      1685832.45      7048613.19
      1686140.55      7049100.69
#Sta/Elev= 30
  4638.6 1425.52  4647.6 1425.97  4653.4 1428.38  4744.5 1434.53  4788.2 1435.12
  4847.5 1430.14  4896.8 1416.26  4918.5 1413.74  4940.3 1406.19  4950.5 1404.70
  4962.0 1397.43  4972.2 1396.39  4978.0 1391.51  4994.0 1385.56  4999.7 1381.48
  5012.9 1380.30  5013.2 1379.80  5017.4 1380.30  5051.6 1384.11  5057.6 1388.41
  5079.0 1394.33  5109.3 1398.33  5130.5 1403.08  5173.6 1407.47  5303.7 1414.32
  5334.0 1414.40  5412.8 1419.57  5428.1 1418.75  5558.7 1423.03  5579.0 1425.48
#Mann=3,-1,0
  4638.6    0.07       0  5012.9    0.07       0  5017.4    0.07       0
Bank Sta=5012.9,5017.4
Exp/Cntr=0.3,0.1

Type RM Length L Ch R = 1,3158,240,240,240
BEGIN DESCRIPTION:
Mapping XS c28c6dc7
END DESCRIPTION:
XS GIS Cut Line= 3
      1685527.73      7048654.82      1685687.27      7048857.77
      1685927.45      7049203.97
#Sta/Elev= 30
  4743.2 1416.63  4750.2 1417.81  4772.7 1417.99  4793.6 1415.44  4799.9 1416.09
  4843.3 1411.92  4878.6 1402.56  4893.0 1400.39  4913.8 1393.39  4942.7 1386.50
  4971.6 1376.48  4990.1 1372.84  4990.5 1372.34  4994.7 1372.84  4998.3 1373.74
  5021.8 1374.41  5050.3 1380.44  5057.6 1384.78  5063.7 1385.54  5072.4 1391.27
  5078.5 1392.30  5086.8 1397.00  5093.4 1399.04  5099.5 1398.99  5150.1 1406.26
  5208.7 1410.06  5283.4 1412.82  5352.8 1416.74  5415.6 1418.94  5422.7 1419.98
#Mann=5,-1,0
  4743.2    0.07       0  4990.1    0.07       0  4994.7    0.07       0
  5208.7    0.16       0  5283.4    0.07       0
Bank Sta=4990.1,4994.7
Exp/Cntr=0.3,0.1

Type RM Length L Ch R = 1,2918,330,330,330
BEGIN DESCRIPTION:
Mapping XS cb737204
END DESCRIPTION:
XS GIS Cut Line= 3
      1685367.15      7048805.65      1685547.30      7049044.40
      1685750.65      7049327.80
#Sta/Elev= 30
  4701.9 1409.61  4794.2 1410.65  4887.9 1406.50  4917.0 1399.04  4923.3 1390.70
  4937.8 1387.33  4944.1 1380.82  4952.4 1379.70  4958.7 1375.42  4997.8 1361.45
  4998.2 1360.95  5002.4 1361.45  5023.3 1368.49  5069.1 1369.68  5103.1 1371.75
  5109.3 1374.73  5124.0 1372.98  5130.2 1375.84  5138.7 1375.70  5144.9 1379.21
  5159.6 1379.98  5180.5 1390.16  5189.1 1391.43  5195.2 1396.13  5208.5 1398.51
  5229.9 1407.34  5251.7 1414.04  5266.5 1416.00  5310.7 1417.71  5349.8 1422.51
#Mann=5,-1,0
  4701.9    0.07       0  4997.8    0.07       0  5002.4    0.07       0
  5069.1    0.16       0  5229.9    0.07       0
Bank Sta=4997.8,5002.4
Exp/Cntr=0.3,0.1

Type RM Length L Ch R = 1,2588,352,352,352
BEGIN DESCRIPTION:
Mapping XS a62c636e
END DESCRIPTION:
XS GIS Cut Line= 3
      1685305.33      7048947.87      1685371.51      7049291.80
      1685413.57      7049564.64
#Sta/Elev= 30
  4652.9 1408.64  4725.4 1407.56  4744.7 1407.35  4787.0 1403.21  4856.7 1392.72
  4866.9 1390.06  4885.7 1380.27  4890.8 1381.50  4897.4 1377.07  4928.0 1364.42
  4942.7 1362.29  4958.5 1356.38  4978.9 1353.70  4990.1 1353.95  5003.1 1355.89
  5017.2 1353.06  5017.5 1352.56  5021.8 1353.06  5039.8 1358.37  5056.9 1368.20
  5061.9 1367.72  5080.2 1377.46  5098.7 1390.29  5120.1 1404.95  5125.1 1404.48
  5130.8 1409.45  5140.9 1413.02  5205.1 1422.44  5232.0 1428.97  5279.2 1434.71
#Mann=7,-1,0
  4652.9    0.07       0  4725.4    0.16       0  4990.1   0.035       0
  5017.2   0.035       0  5021.8   0.035       0  5098.7    0.07       0
  5205.1   0.035       0
Bank Sta=5017.2,5021.8
Exp/Cntr=0.3,0.1

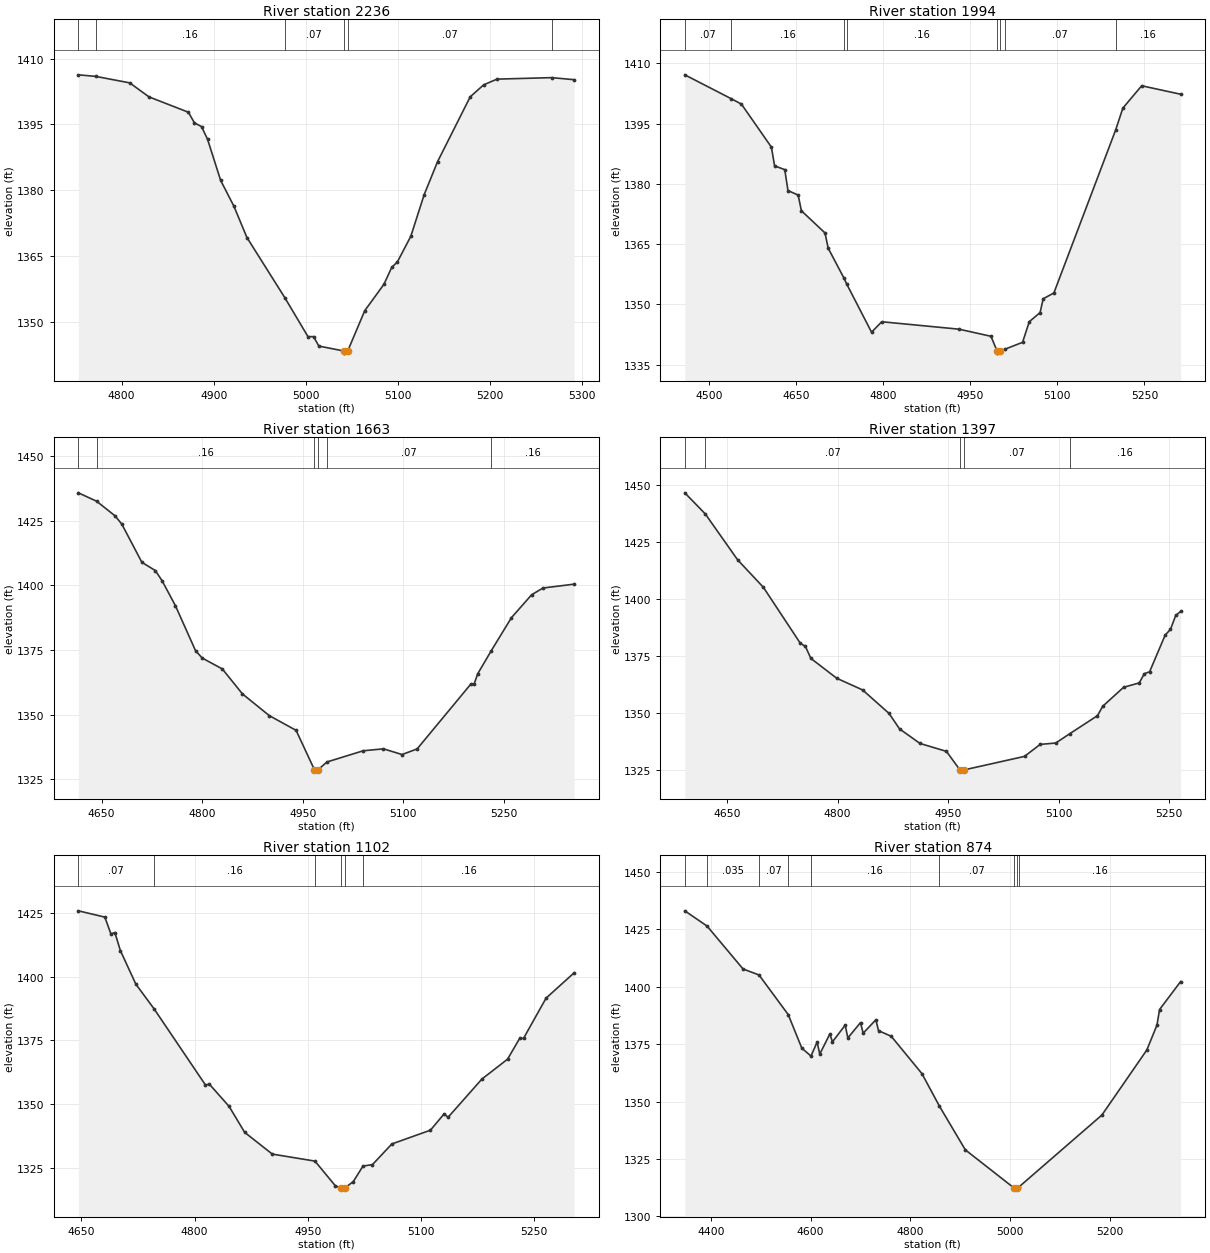
Type RM Length L Ch R = 1,2236,242,242,242
BEGIN DESCRIPTION:
Mapping XS f43d9b37
END DESCRIPTION:
XS GIS Cut Line= 3
      1685229.35      7048964.13      1685066.61      7049153.99
      1684892.69      7049384.09
#Sta/Elev= 30
  4753.0 1406.30  4771.7 1405.95  4808.8 1404.47  4829.7 1401.28  4872.5 1397.78
  4879.1 1395.36  4886.8 1394.50  4893.3 1391.64  4907.6 1382.23  4921.9 1376.40
  4936.1 1369.24  4977.2 1355.55  5002.4 1346.66  5008.5 1346.66  5014.2 1344.51
  5041.0 1343.40  5041.3 1342.90  5045.6 1343.40  5064.1 1352.58  5085.0 1358.61
  5093.3 1362.42  5099.5 1363.67  5114.1 1369.52  5128.6 1379.00  5143.2 1386.54
  5178.6 1401.29  5193.2 1404.02  5207.7 1405.32  5267.0 1405.66  5291.5 1405.19
#Mann=6,-1,0
  4753.0    0.07       0  4771.7    0.16       0  4977.2    0.07       0
  5041.0    0.07       0  5045.6    0.07       0  5267.0    0.16       0
Bank Sta=5041,5045.6
Exp/Cntr=0.3,0.1

Type RM Length L Ch R = 1,1994,331,331,331
BEGIN DESCRIPTION:
Mapping XS 107514d5
END DESCRIPTION:
XS GIS Cut Line= 3
      1685121.95      7048487.76      1684896.25      7048984.72
      1684779.52      7049270.06
#Sta/Elev= 30
  4458.3 1407.13  4538.5 1401.17  4555.8 1399.85  4607.5 1389.13  4613.0 1384.46
  4630.5 1383.54  4636.0 1378.33  4653.6 1377.20  4659.1 1373.31  4699.8 1367.78
  4705.3 1363.98  4732.7 1356.48  4737.4 1355.01  4780.0 1343.08  4797.6 1345.68
  4930.8 1343.83  4985.7 1342.06  4996.3 1338.37  4996.6 1337.87  5000.9 1338.37
  5009.1 1338.81  5040.1 1340.56  5051.7 1345.69  5070.3 1347.96  5075.7 1351.40
  5094.1 1352.85  5200.6 1393.45  5212.9 1398.85  5245.3 1404.41  5312.4 1402.30
#Mann=8,-1,0
  4458.3    0.07       0  4538.5    0.16       0  4732.7    0.07       0
  4737.4    0.16       0  4996.3    0.07       0  5000.9    0.16       0
  5009.1    0.07       0  5200.6    0.16       0
Bank Sta=4996.3,5000.9
Exp/Cntr=0.3,0.1

Type RM Length L Ch R = 1,1663,266,266,266
BEGIN DESCRIPTION:
Mapping XS 461ac10c
END DESCRIPTION:
XS GIS Cut Line= 3
      1684690.63      7048353.21      1684690.63      7048740.58
      1684724.27      7049091.10
#Sta/Elev= 30
  4615.2 1435.84  4642.4 1432.60  4670.0 1426.92  4680.0 1423.74  4710.0 1408.93
  4730.0 1405.76  4740.0 1401.86  4760.0 1392.14  4790.0 1374.73  4800.0 1371.87
  4830.0 1367.64  4860.0 1357.98  4900.0 1349.58  4940.0 1343.88  4967.4 1328.59
  4967.8 1328.09  4972.5 1328.59  4986.1 1331.64  5040.2 1335.98  5070.3 1336.72
  5098.0 1334.51  5120.5 1336.69  5200.6 1361.79  5205.6 1361.90  5210.9 1365.80
  5231.0 1374.68  5261.2 1387.52  5291.3 1396.38  5308.2 1398.99  5354.7 1400.48
#Mann=6,-1,0
  4615.2    0.07       0  4642.4    0.16       0  4967.4    0.07       0
  4972.5    0.16       0  4986.1    0.07       0  5231.0    0.16       0
Bank Sta=4967.4,4972.5
Exp/Cntr=0.3,0.1

Type RM Length L Ch R = 1,1397,295,295,295
BEGIN DESCRIPTION:
Mapping XS 8e5d0372
END DESCRIPTION:
XS GIS Cut Line= 3
      1684196.90      7048615.05      1684500.75      7048886.34
      1684688.46      7049074.05
#Sta/Elev= 30
  4592.7 1446.37  4620.5 1437.12  4664.3 1417.02  4699.4 1404.91  4749.6 1380.33
  4756.3 1379.07  4763.8 1373.75  4798.9 1365.05  4834.0 1359.93  4869.9 1349.62
  4884.1 1342.85  4911.9 1336.46  4947.7 1333.00  4966.1 1324.83  4966.5 1324.33
  4971.2 1324.83  5053.7 1330.80  5074.9 1336.05  5096.1 1336.66  5115.2 1340.77
  5152.7 1348.66  5159.8 1352.77  5188.1 1361.09  5209.3 1363.01  5216.3 1367.06
  5223.4 1367.90  5244.6 1384.04  5251.7 1386.45  5258.8 1392.58  5265.5 1394.36
#Mann=5,-1,0
  4592.7    0.16       0  4620.5    0.07       0  4966.1    0.07       0
  4971.2    0.07       0  5115.2    0.16       0
Bank Sta=4966.1,4971.2
Exp/Cntr=0.3,0.1

Type RM Length L Ch R = 1,1102,228,228,228
BEGIN DESCRIPTION:
Mapping XS b3677e11
END DESCRIPTION:
XS GIS Cut Line= 3
      1684110.92      7049082.07      1684453.37      7049165.40
      1684751.40      7049227.60
#Sta/Elev= 30
  4645.9 1425.77  4681.0 1423.31  4689.1 1416.69  4694.3 1417.26  4701.6 1410.18
  4722.1 1397.02  4746.5 1387.22  4814.3 1357.48  4819.5 1357.80  4845.6 1349.08
  4866.3 1338.88  4902.9 1330.36  4959.4 1327.61  4986.4 1317.93  4994.1 1317.12
  4994.5 1316.62  4999.2 1317.12  5010.2 1319.59  5023.0 1325.65  5035.6 1326.25
  5061.3 1334.34  5112.4 1339.74  5130.6 1346.16  5135.7 1344.78  5180.6 1359.80
  5214.5 1367.57  5230.6 1375.72  5235.7 1375.74  5265.6 1391.53  5302.8 1401.47
#Mann=6,-1,0
  4645.9    0.07       0  4746.5    0.16       0  4959.4    0.07       0
  4994.1    0.07       0  4999.2    0.07       0  5023.0    0.16       0
Bank Sta=4994.1,4999.2
Exp/Cntr=0.3,0.1

Type RM Length L Ch R = 1,874,155,155,155
BEGIN DESCRIPTION:
Mapping XS 1668d160
END DESCRIPTION:
XS GIS Cut Line= 3
      1683840.59      7049173.45      1684454.56      7049393.18
      1684791.74      7049335.96
#Sta/Elev= 30
  4347.9 1432.97  4392.5 1426.35  4464.7 1407.67  4496.7 1405.07  4555.3 1387.81
  4582.5 1373.24  4600.9 1369.79  4613.2 1375.89  4618.5 1370.65  4638.7 1379.39
  4644.0 1375.99  4669.5 1383.25  4674.8 1377.67  4700.2 1384.35  4705.5 1379.74
  4731.0 1385.56  4736.3 1380.84  4761.8 1378.39  4823.3 1362.16  4858.5 1347.97
  4910.3 1329.00  5008.0 1312.40  5008.4 1311.90  5013.1 1312.40  5017.1 1312.71
  5184.2 1344.14  5274.3 1372.45  5294.6 1383.29  5299.8 1390.04  5342.0 1402.20
#Mann=9,-1,0
  4347.9    0.07       0  4392.5   0.035       0  4496.7    0.07       0
  4555.3   0.035       0  4600.9    0.16       0  4858.5    0.07       0
  5008.0    0.07       0  5013.1    0.07       0  5017.1    0.16       0
Bank Sta=5008,5013.1
Exp/Cntr=0.3,0.1

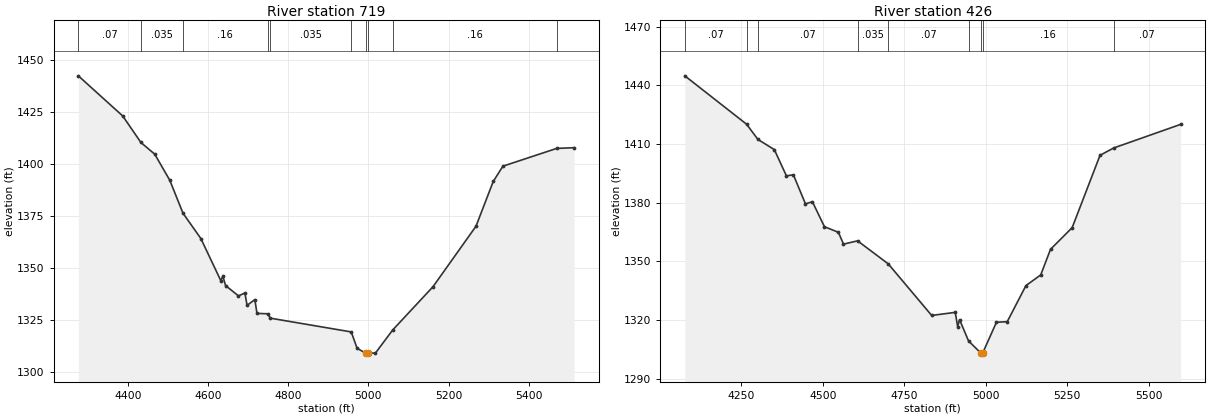
Type RM Length L Ch R = 1,719,293,293,293
BEGIN DESCRIPTION:
Mapping XS 66eac4bb
END DESCRIPTION:
XS GIS Cut Line= 3
      1683831.85      7049275.42      1684507.79      7049532.30
      1685008.15      7049418.65
#Sta/Elev= 30
  4276.9 1442.44  4387.6 1423.15  4432.9 1410.42  4467.3 1404.82  4504.9 1392.28
  4537.8 1376.45  4582.4 1364.26  4632.0 1344.08  4637.3 1346.13  4644.0 1341.68
  4676.1 1336.72  4692.2 1338.09  4697.6 1332.17  4717.0 1334.92  4722.3 1328.30
  4748.7 1328.12  4755.7 1326.00  4957.3 1319.40  4972.0 1311.51  4993.2 1309.23
  4993.6 1308.73  4998.5 1309.23  5017.6 1309.23  5060.6 1320.31  5161.2 1341.13
  5268.3 1370.16  5311.4 1391.70  5335.5 1399.03  5469.6 1407.57  5513.1 1407.91
#Mann=10,-1,0
  4276.9    0.07       0  4432.9   0.035       0  4537.8    0.16       0
  4748.7    0.07       0  4755.7   0.035       0  4957.3    0.07       0
  4993.2    0.07       0  4998.5    0.07       0  5060.6    0.16       0
  5469.6    0.07       0
Bank Sta=4993.2,4998.5
Exp/Cntr=0.3,0.1

Type RM Length L Ch R = 1,426,0,0,0
BEGIN DESCRIPTION:
Mapping XS b2d935a2
END DESCRIPTION:
XS GIS Cut Line= 3
      1683812.34      7049323.17      1684603.43      7049795.29
      1685145.67      7049538.10
#Sta/Elev= 30
  4076.9 1444.79  4266.6 1420.04  4301.3 1412.27  4351.7 1407.06  4388.7 1393.66
  4410.1 1394.19  4447.1 1379.36  4468.5 1380.41  4505.5 1367.64  4548.3 1364.80
  4563.8 1358.75  4607.1 1360.43  4701.1 1348.67  4834.4 1322.30  4906.8 1323.87
  4914.1 1316.64  4920.0 1320.12  4947.5 1309.29  4985.5 1303.02  4985.9 1302.52
  4990.8 1303.02  5033.1 1318.79  5066.3 1319.12  5123.7 1337.55  5169.1 1343.03
  5199.1 1356.10  5265.6 1367.20  5351.0 1404.17  5393.0 1407.91  5598.3 1419.97
#Mann=9,-1,0
  4076.9    0.07       0  4266.6   0.035       0  4301.3    0.07       0
  4607.1   0.035       0  4701.1    0.07       0  4947.5    0.16       0
  4985.5    0.07       0  4990.8    0.16       0  5393.0    0.07       0
Bank Sta=4985.5,4990.8
Exp/Cntr=0.3,0.1

Chan Stop Cuts=-1