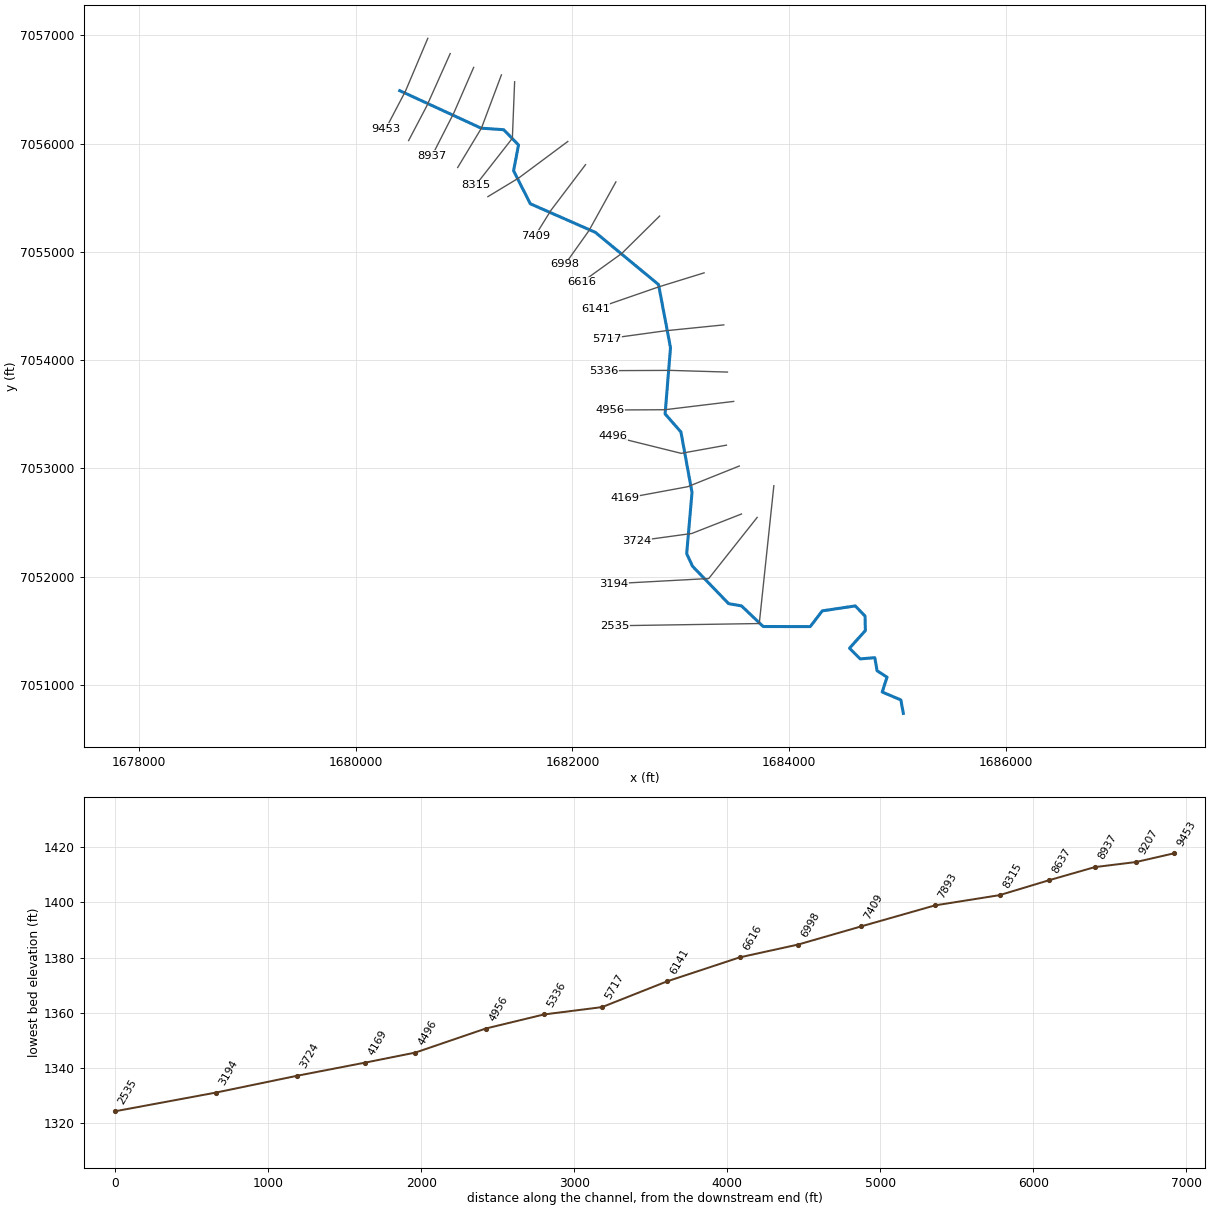
--- Chimney Creek 1194.prj (project) ---

Proj Title=Chimney Creek 1194 Base Level Engineering
Current Plan=p01
Default Exp/Contr=0.3,0.1
English Units
Geom File=g01
Flow File=f01
Plan File=p01
BEGIN DESCRIPTION:
Chimney Creek 1194
END DESCRIPTION:

--- Chimney Creek 1194.p01 (plan) ---

Plan Title=Multiple Run
Short Identifier=Multiple
Geom File=g01
Flow File=f01
Subcritical Flow
K Sum by GR= 0
Std Step Tol= 0.01
Critical Tol= 0.01
Num of Std Step Trials= 20
Max Error Tol= 0.3
Flow Tol Ratio= 0.001
Split Flow NTrial= 30
Split Flow Tol= 0.02
Split Flow Ratio= 0.02
Log Output Level= 0
Friction Slope Method= 1
Unsteady Friction Slope Method= 2
Unsteady Bridges Friction Slope Method= 1
Parabolic Critical Depth
Global Vel Dist=  1 , 1 , 1
Global Log Level= 0
CheckData=True
Encroach Param= -1, 0, 0, 0
BEGIN DESCRIPTION:
Multiple Run
END DESCRIPTION:

--- Chimney Creek 1194.f01 (steady flow) ---

Flow Title=Multiple
Number of Profiles=7
Profile Names=10-year,25-year,50-year,1pct_min,100-year,1pct_plu,500-year
River Rch & RM= Chimney Creek 11,Reach-1,9453
     741    1087    1390     883    1761    3514    2851
Boundary for River Rch & Prof#=Chimney Creek 11,Reach-1,1
Up Type=0
Dn Type=3
Dn Slope=0.005
Boundary for River Rch & Prof#=Chimney Creek 11,Reach-1,2
Up Type=0
Dn Type=3
Dn Slope=0.005
Boundary for River Rch & Prof#=Chimney Creek 11,Reach-1,3
Up Type=0
Dn Type=3
Dn Slope=0.005
Boundary for River Rch & Prof#=Chimney Creek 11,Reach-1,4
Up Type=0
Dn Type=3
Dn Slope=0.005
Boundary for River Rch & Prof#=Chimney Creek 11,Reach-1,5
Up Type=0
Dn Type=3
Dn Slope=0.005
Boundary for River Rch & Prof#=Chimney Creek 11,Reach-1,6
Up Type=0
Dn Type=3
Dn Slope=0.005
Boundary for River Rch & Prof#=Chimney Creek 11,Reach-1,7
Up Type=0
Dn Type=3
Dn Slope=0.005

--- Chimney Creek 1194.g01 (geometry) ---

Geom Title=Existing Conditions

River Reach=Chimney Creek 11,Reach-1
Reach XY= 30
      1680405.00      7056488.00      1681156.55      7056141.75
      1681364.80      7056127.52      1681501.87      7055986.37
      1681456.20      7055748.51      1681610.61      7055443.59
      1682211.05      7055179.84      1682794.52      7054697.80
      1682905.09      7054115.31      1682855.38      7053503.16
      1683001.46      7053336.54      1683103.78      7052777.50
      1683054.58      7052212.99      1683108.51      7052096.48
      1683441.70      7051751.40      1683561.17      7051730.14
      1683760.85      7051540.06      1684195.57      7051539.14
      1684306.28      7051684.48      1684611.21      7051730.20
      1684701.48      7051636.54      1684704.69      7051503.04
      1684558.08      7051339.66      1684656.63      7051241.15
      1684791.61      7051252.12      1684812.80      7051131.57
      1684904.75      7051071.98      1684859.98      7050935.42
      1685032.34      7050862.05      1685055.00      7050738.00

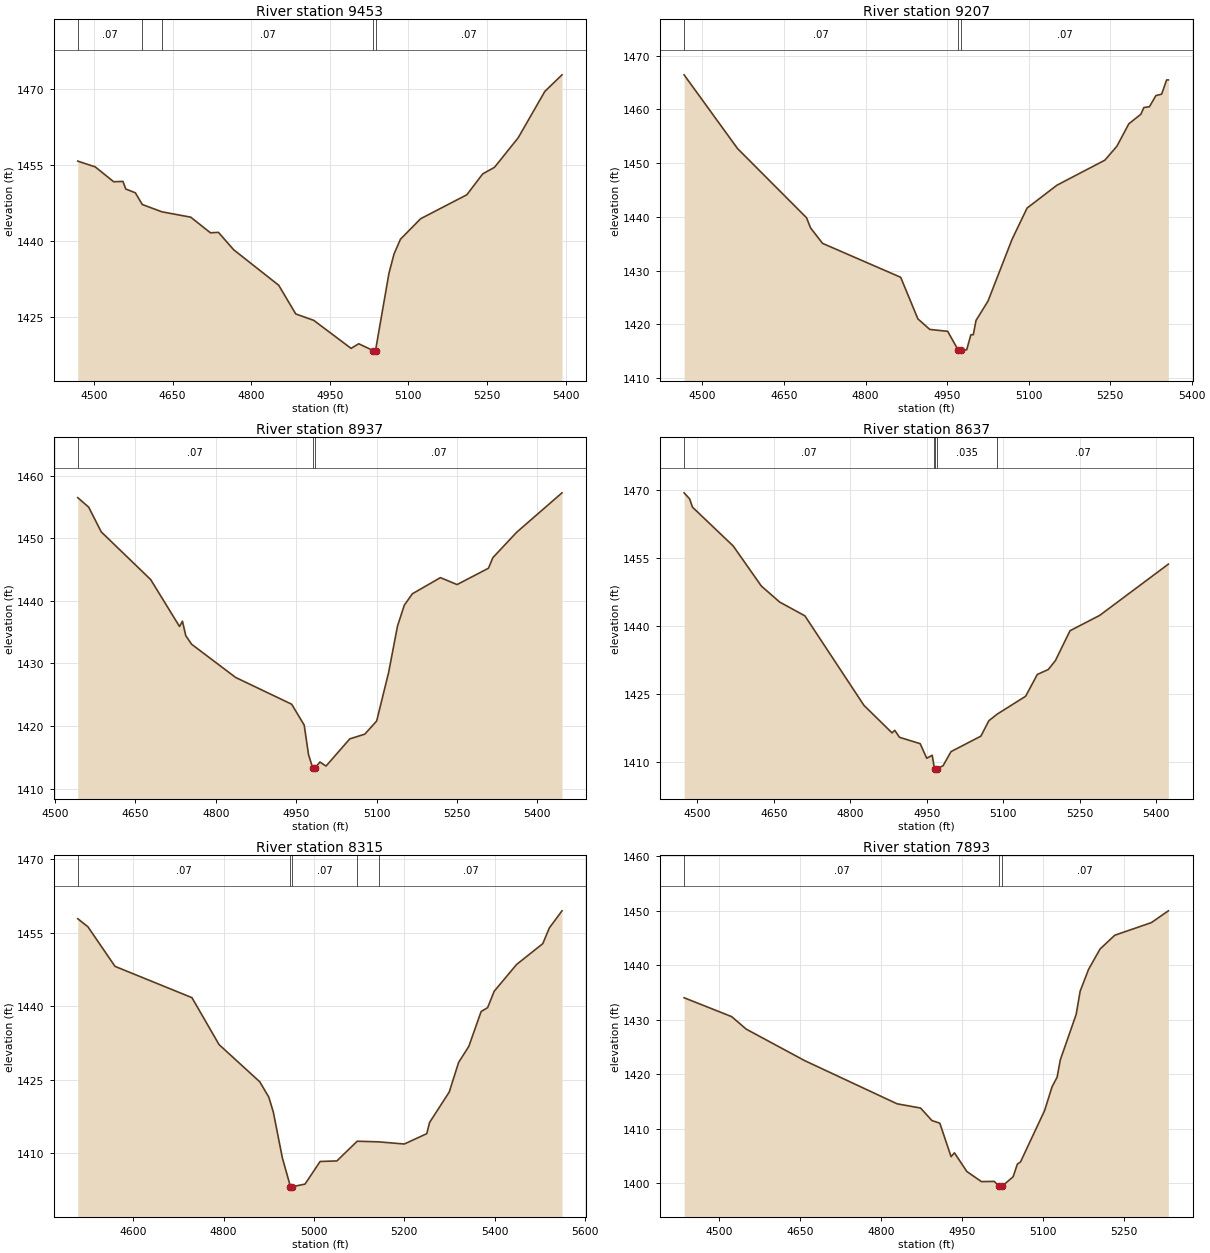
Type RM Length L Ch R = 1,9453,246,246,246
BEGIN DESCRIPTION:
Chimney Creek 1194 20.0
END DESCRIPTION:
XS GIS Cut Line= 3
      1680664.12      7056971.20      1680457.36      7056482.32
      1680274.80      7056133.96
#Sta/Elev= 30
  4469.2 1455.72  4502.6 1454.58  4537.8 1451.64  4555.4 1451.71  4560.9 1450.20
  4579.1 1449.46  4592.4 1447.14  4629.7 1445.70  4684.8 1444.64  4722.4 1441.55
  4737.6 1441.64  4766.7 1438.20  4852.7 1431.18  4885.2 1425.51  4919.7 1424.23
  4990.8 1418.70  5005.3 1419.61  5033.2 1418.26  5033.4 1417.76  5037.4 1418.26
  5063.0 1433.51  5072.6 1437.32  5085.0 1440.28  5123.5 1444.33  5211.7 1449.07
  5242.0 1453.20  5264.5 1454.50  5309.7 1460.34  5360.5 1469.50  5393.3 1472.78
#Mann=5,-1,0
  4469.2    0.07       0  4592.4    0.16       0  4629.7    0.07       0
  5033.2    0.07       0  5037.4    0.07       0
Bank Sta=5033.2,5037.4
Exp/Cntr=0.3,0.1

Type RM Length L Ch R = 1,9207,270,270,270
BEGIN DESCRIPTION:
Mapping XS 760085a0
END DESCRIPTION:
XS GIS Cut Line= 3
      1680871.13      7056830.53      1680653.71      7056344.90
      1680487.02      7056027.15
#Sta/Elev= 30
  4466.2 1466.42  4564.5 1452.71  4691.4 1439.84  4699.1 1437.91  4721.0 1435.06
  4864.7 1428.75  4896.3 1421.02  4918.2 1419.05  4951.1 1418.70  4970.9 1415.14
  4971.1 1414.64  4975.1 1415.14  4986.1 1415.26  4993.8 1418.06  4998.3 1418.06
  5003.3 1420.72  5025.4 1424.34  5069.5 1435.80  5097.2 1441.63  5152.1 1445.88
  5240.3 1450.54  5262.4 1453.13  5284.4 1457.31  5306.5 1459.08  5312.1 1460.34
  5322.3 1460.48  5334.2 1462.56  5344.8 1462.83  5353.9 1465.47  5357.1 1465.47
#Mann=3,-1,0
  4466.2    0.07       0  4970.9    0.07       0  4975.1    0.07       0
Bank Sta=4970.9,4975.1
Exp/Cntr=0.3,0.1

Type RM Length L Ch R = 1,8937,300,300,300
BEGIN DESCRIPTION:
Mapping XS be73ed0b
END DESCRIPTION:
XS GIS Cut Line= 3
      1681087.67      7056702.83      1680905.39      7056284.02
      1680702.48      7055885.80
#Sta/Elev= 30
  4542.5 1456.52  4562.9 1455.00  4586.4 1451.04  4678.6 1443.42  4732.4 1435.92
  4737.9 1436.77  4744.1 1434.45  4755.0 1433.08  4837.1 1427.77  4941.7 1423.49
  4965.1 1420.15  4973.1 1415.46  4981.0 1413.29  4981.3 1412.79  4985.3 1413.29
  4994.4 1414.25  5005.8 1413.60  5050.2 1417.95  5078.1 1418.70  5100.3 1420.80
  5122.6 1428.56  5139.2 1435.98  5151.9 1439.33  5167.0 1441.15  5219.3 1443.73
  5250.4 1442.62  5309.0 1445.24  5317.1 1446.92  5361.5 1450.98  5446.2 1457.29
#Mann=3,-1,0
  4542.5    0.07       0  4981.0    0.07       0  4985.3    0.07       0
Bank Sta=4981,4985.3
Exp/Cntr=0.3,0.1

Type RM Length L Ch R = 1,8637,322,322,322
BEGIN DESCRIPTION:
Mapping XS 86209e96
END DESCRIPTION:
XS GIS Cut Line= 3
      1681343.77      7056633.45      1681159.29      7056141.88
      1680940.12      7055778.39
#Sta/Elev= 30
  4473.9 1469.33  4484.8 1467.99  4490.4 1466.17  4570.3 1457.61  4625.4 1448.79
  4661.3 1445.27  4710.8 1442.23  4826.5 1422.52  4881.7 1416.44  4887.0 1417.01
  4896.3 1415.47  4936.8 1414.07  4949.7 1410.85  4960.4 1411.52  4963.2 1409.65
  4964.9 1408.52  4965.2 1408.02  4969.2 1408.52  4981.7 1409.21  4997.3 1412.32
  5055.9 1415.73  5071.4 1419.12  5087.6 1420.56  5143.6 1424.52  5166.5 1429.32
  5187.9 1430.40  5202.0 1432.38  5230.6 1438.95  5288.8 1442.33  5423.4 1453.62
#Mann=5,-1,0
  4473.9    0.07       0  4963.2   0.035       0  4964.9   0.035       0
  4969.2   0.035       0  5087.6    0.07       0
Bank Sta=4964.9,4969.2
Exp/Cntr=0.3,0.1

Type RM Length L Ch R = 1,8315,422,422,422
BEGIN DESCRIPTION:
Mapping XS 4a5fa957
END DESCRIPTION:
XS GIS Cut Line= 3
      1681465.84      7056570.47      1681445.01      7056048.36
      1681106.47      7055616.07
#Sta/Elev= 30
  4477.4 1457.89  4499.9 1456.24  4559.9 1448.15  4730.1 1441.76  4790.1 1432.17
  4880.2 1424.57  4900.2 1421.43  4910.2 1418.38  4930.2 1409.01  4948.1 1403.14
  4948.4 1402.64  4952.4 1403.14  4980.3 1403.67  5013.7 1408.29  5050.8 1408.40
  5095.8 1412.43  5143.2 1412.30  5200.0 1411.86  5249.7 1413.97  5256.0 1416.27
  5299.4 1422.47  5320.2 1428.53  5342.8 1431.81  5370.0 1438.93  5384.4 1439.72
  5398.9 1443.07  5448.6 1448.55  5506.5 1452.80  5520.9 1456.00  5549.0 1459.50
#Mann=5,-1,0
  4477.4    0.07       0  4948.1    0.07       0  4952.4    0.07       0
  5095.8   0.035       0  5143.2    0.07       0
Bank Sta=4948.1,4952.4
Exp/Cntr=0.3,0.1

Type RM Length L Ch R = 1,7893,484,484,484
BEGIN DESCRIPTION:
Mapping XS 468d82b6
END DESCRIPTION:
XS GIS Cut Line= 3
      1681956.66      7056018.63      1681503.10      7055681.18
      1681218.83      7055509.32
#Sta/Elev= 30
  4434.4 1434.05  4522.5 1430.59  4549.6 1428.29  4658.1 1422.50  4829.1 1414.59
  4872.7 1413.81  4893.8 1411.51  4908.4 1411.03  4929.2 1404.89  4935.5 1405.59
  4958.4 1402.17  4985.5 1400.31  5009.2 1400.35  5018.8 1399.43  5019.1 1398.93
  5023.4 1399.43  5044.2 1401.20  5052.1 1403.52  5058.0 1403.94  5102.7 1413.38
  5116.2 1417.67  5125.8 1419.49  5131.7 1422.66  5161.1 1431.00  5168.5 1435.27
  5184.1 1439.27  5205.4 1443.00  5232.6 1445.52  5300.5 1447.84  5331.9 1450.00
#Mann=3,-1,0
  4434.4    0.07       0  5018.8    0.07       0  5023.4    0.07       0
Bank Sta=5018.8,5023.4
Exp/Cntr=0.3,0.1

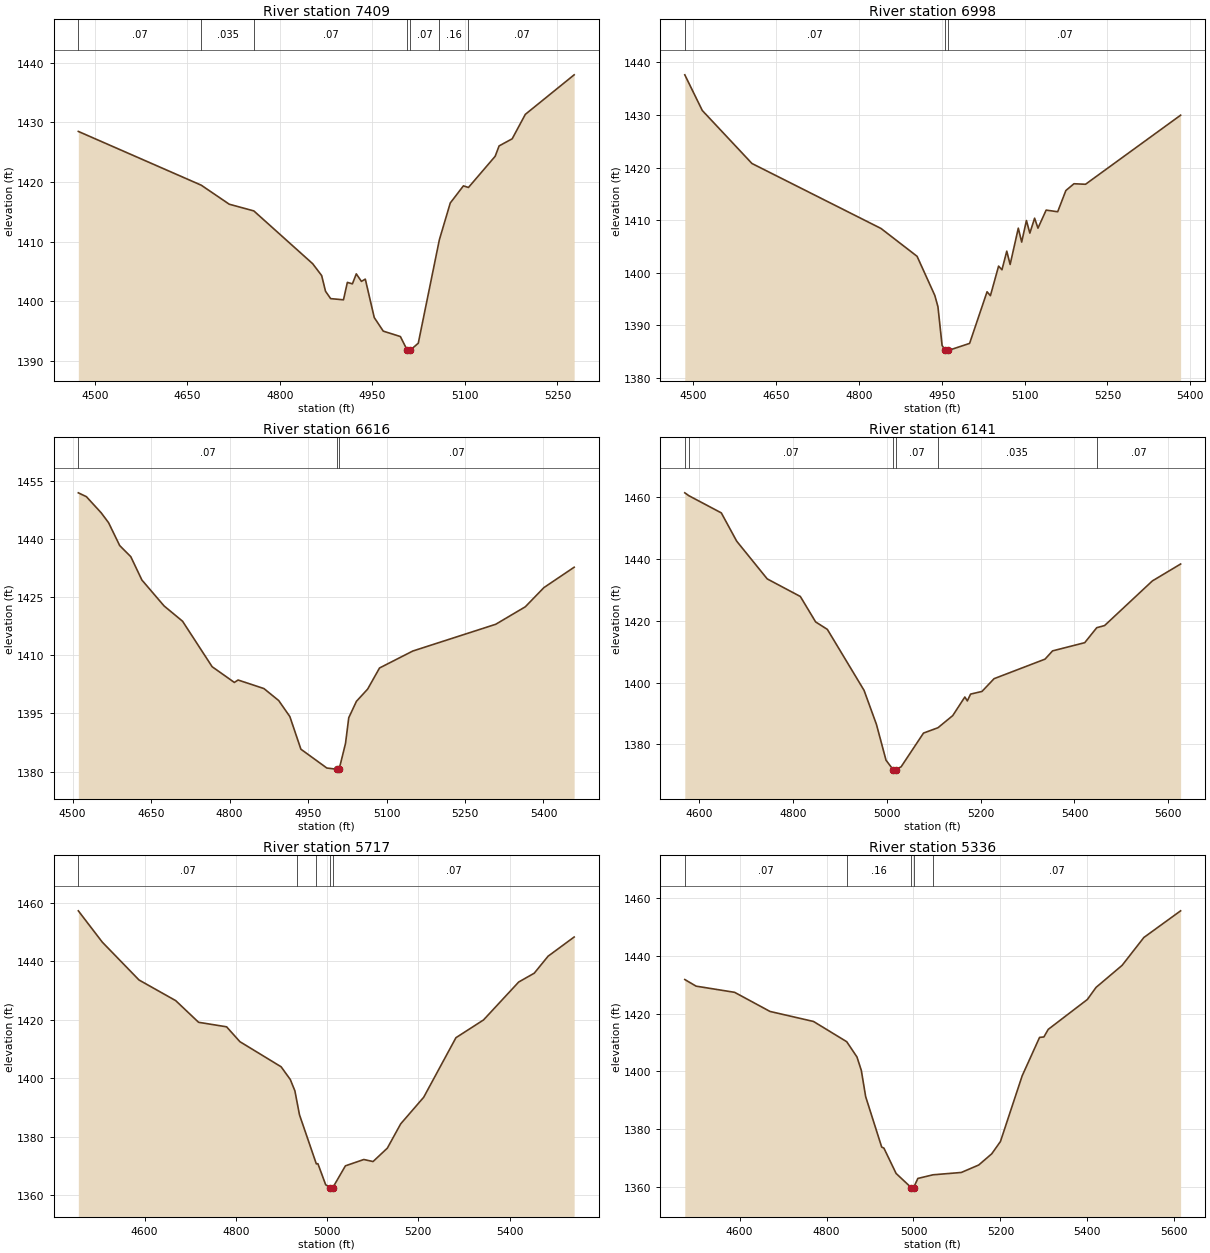
Type RM Length L Ch R = 1,7409,411,411,411
BEGIN DESCRIPTION:
Mapping XS afaa09b0
END DESCRIPTION:
XS GIS Cut Line= 3
      1682120.52      7055804.61      1681801.49      7055383.58
      1681656.07      7055149.17
#Sta/Elev= 30
  4473.0 1428.48  4672.4 1419.46  4717.8 1416.27  4757.6 1415.15  4853.1 1406.29
  4867.6 1404.31  4873.9 1401.67  4882.2 1400.44  4903.0 1400.24  4909.3 1403.16
  4917.5 1402.92  4923.8 1404.59  4932.1 1403.33  4938.4 1403.71  4952.9 1397.27
  4967.5 1394.99  4995.3 1394.08  5006.4 1391.80  5006.8 1391.30  5011.3 1391.80
  5024.3 1392.96  5058.5 1410.31  5076.2 1416.48  5097.5 1419.35  5105.7 1419.08
  5149.0 1424.31  5155.4 1426.05  5176.6 1427.24  5197.9 1431.34  5277.1 1437.97
#Mann=7,-1,0
  4473.0    0.07       0  4672.4   0.035       0  4757.6    0.07       0
  5006.4    0.07       0  5011.3    0.07       0  5058.5    0.16       0
  5105.7    0.07       0
Bank Sta=5006.4,5011.3
Exp/Cntr=0.3,0.1

Type RM Length L Ch R = 1,6998,382,382,382
BEGIN DESCRIPTION:
Mapping XS 22cf94ea
END DESCRIPTION:
XS GIS Cut Line= 3
      1682400.93      7055645.71      1682151.39      7055194.36
      1681930.04      7054882.95
#Sta/Elev= 30
  4484.8 1437.63  4516.5 1430.85  4606.4 1420.78  4840.1 1408.43  4905.4 1403.14
  4937.5 1395.71  4943.2 1393.55  4950.7 1386.19  4956.8 1385.24  4957.1 1384.74
  4961.7 1385.24  5000.5 1386.59  5032.1 1396.40  5038.2 1395.66  5053.0 1401.28
  5059.1 1400.58  5067.8 1404.12  5073.9 1401.59  5088.7 1408.49  5094.8 1405.85
  5103.4 1409.94  5109.6 1407.55  5118.2 1410.38  5124.3 1408.49  5139.1 1411.92
  5160.0 1411.61  5174.8 1415.64  5189.5 1416.93  5210.4 1416.83  5382.6 1429.96
#Mann=3,-1,0
  4484.8    0.07       0  4956.8    0.07       0  4961.7    0.07       0
Bank Sta=4956.8,4961.7
Exp/Cntr=0.3,0.1

Type RM Length L Ch R = 1,6616,475,475,475
BEGIN DESCRIPTION:
Mapping XS 9c50bdc5
END DESCRIPTION:
XS GIS Cut Line= 3
      1682804.61      7055330.21      1682455.64      7054985.16
      1682084.53      7054718.22
#Sta/Elev= 30
  4510.8 1451.96  4526.2 1450.97  4554.5 1446.80  4568.6 1444.25  4589.9 1438.34
  4611.1 1435.47  4632.3 1429.45  4674.7 1422.76  4710.1 1418.80  4766.6 1407.06
  4809.1 1403.00  4816.2 1403.63  4865.6 1401.42  4893.9 1398.32  4915.2 1394.18
  4936.3 1385.76  4985.9 1380.90  5004.4 1380.60  5004.7 1380.10  5009.4 1380.60
  5021.6 1387.26  5027.8 1393.90  5042.5 1398.13  5063.9 1401.28  5086.6 1406.73
  5150.2 1411.11  5308.8 1418.02  5365.3 1422.53  5400.9 1427.49  5458.7 1432.75
#Mann=3,-1,0
  4510.8    0.07       0  5004.4    0.07       0  5009.4    0.07       0
Bank Sta=5004.4,5009.4
Exp/Cntr=0.3,0.1

Type RM Length L Ch R = 1,6141,424,424,424
BEGIN DESCRIPTION:
Mapping XS 2f080eb0
END DESCRIPTION:
XS GIS Cut Line= 3
      1683215.45      7054805.69      1682800.93      7054677.65
      1682211.79      7054473.67
#Sta/Elev= 30
  4569.1 1461.23  4577.8 1460.30  4647.0 1454.75  4679.7 1445.64  4744.9 1433.44
  4815.5 1427.77  4848.1 1419.56  4873.1 1417.15  4951.3 1397.49  4977.8 1386.47
  4998.2 1374.92  5013.3 1371.90  5013.7 1371.40  5018.4 1371.90  5030.4 1372.80
  5078.1 1383.68  5109.0 1385.41  5140.5 1389.33  5166.3 1395.33  5171.6 1394.06
  5178.5 1396.26  5202.8 1397.12  5228.6 1401.24  5337.3 1407.55  5353.3 1410.21
  5421.9 1412.86  5447.5 1417.69  5464.3 1418.39  5566.1 1432.79  5626.4 1438.25
#Mann=6,-1,0
  4569.1    0.16       0  4577.8    0.07       0  5013.3    0.07       0
  5018.4    0.07       0  5109.0   0.035       0  5447.5    0.07       0
Bank Sta=5013.3,5018.4
Exp/Cntr=0.3,0.1

Type RM Length L Ch R = 1,5717,381,381,381
BEGIN DESCRIPTION:
Mapping XS c783f3a7
END DESCRIPTION:
XS GIS Cut Line= 3
      1683397.30      7054325.26      1682855.62      7054270.57
      1682318.32      7054196.59
#Sta/Elev= 30
  4454.8 1457.34  4507.4 1446.61  4587.8 1433.67  4668.2 1426.61  4718.4 1419.19
  4779.8 1417.64  4808.9 1412.56  4899.3 1403.96  4919.4 1399.61  4929.5 1395.72
  4934.8 1391.39  4939.5 1387.55  4976.5 1370.72  4979.9 1370.80  4997.0 1363.58
  5007.4 1362.59  5007.8 1362.09  5012.5 1362.59  5040.2 1370.06  5080.6 1372.23
  5100.8 1371.53  5132.1 1376.12  5161.4 1384.43  5211.8 1393.53  5282.5 1413.92
  5343.0 1420.00  5420.0 1432.97  5454.1 1435.99  5484.4 1441.80  5541.6 1448.38
#Mann=5,-1,0
  4454.8    0.07       0  4934.8    0.16       0  4976.5    0.07       0
  5007.4    0.07       0  5012.5    0.07       0
Bank Sta=5007.4,5012.5
Exp/Cntr=0.3,0.1

Type RM Length L Ch R = 1,5336,380,380,380
BEGIN DESCRIPTION:
Mapping XS 0c86932d
END DESCRIPTION:
XS GIS Cut Line= 3
      1683431.03      7053889.49      1682904.99      7053905.12
      1682290.37      7053902.51
#Sta/Elev= 30
  4473.8 1431.73  4499.8 1429.45  4588.4 1427.32  4669.9 1420.72  4770.0 1417.26
  4846.4 1410.28  4870.0 1405.00  4880.0 1400.37  4890.0 1391.31  4926.9 1373.91
  4931.9 1373.58  4960.0 1364.82  4995.0 1359.91  4995.4 1359.41  5000.2 1359.91
  5010.1 1363.10  5044.8 1364.35  5110.1 1365.16  5150.1 1367.73  5180.1 1371.60
  5200.1 1375.84  5250.1 1398.51  5290.1 1411.76  5300.1 1411.92  5310.1 1414.54
  5400.1 1424.85  5420.1 1429.02  5480.1 1436.63  5530.1 1446.24  5614.7 1455.44
#Mann=5,-1,0
  4473.8    0.07       0  4846.4    0.16       0  4995.0    0.07       0
  5000.2    0.16       0  5044.8    0.07       0
Bank Sta=4995,5000.2
Exp/Cntr=0.3,0.1

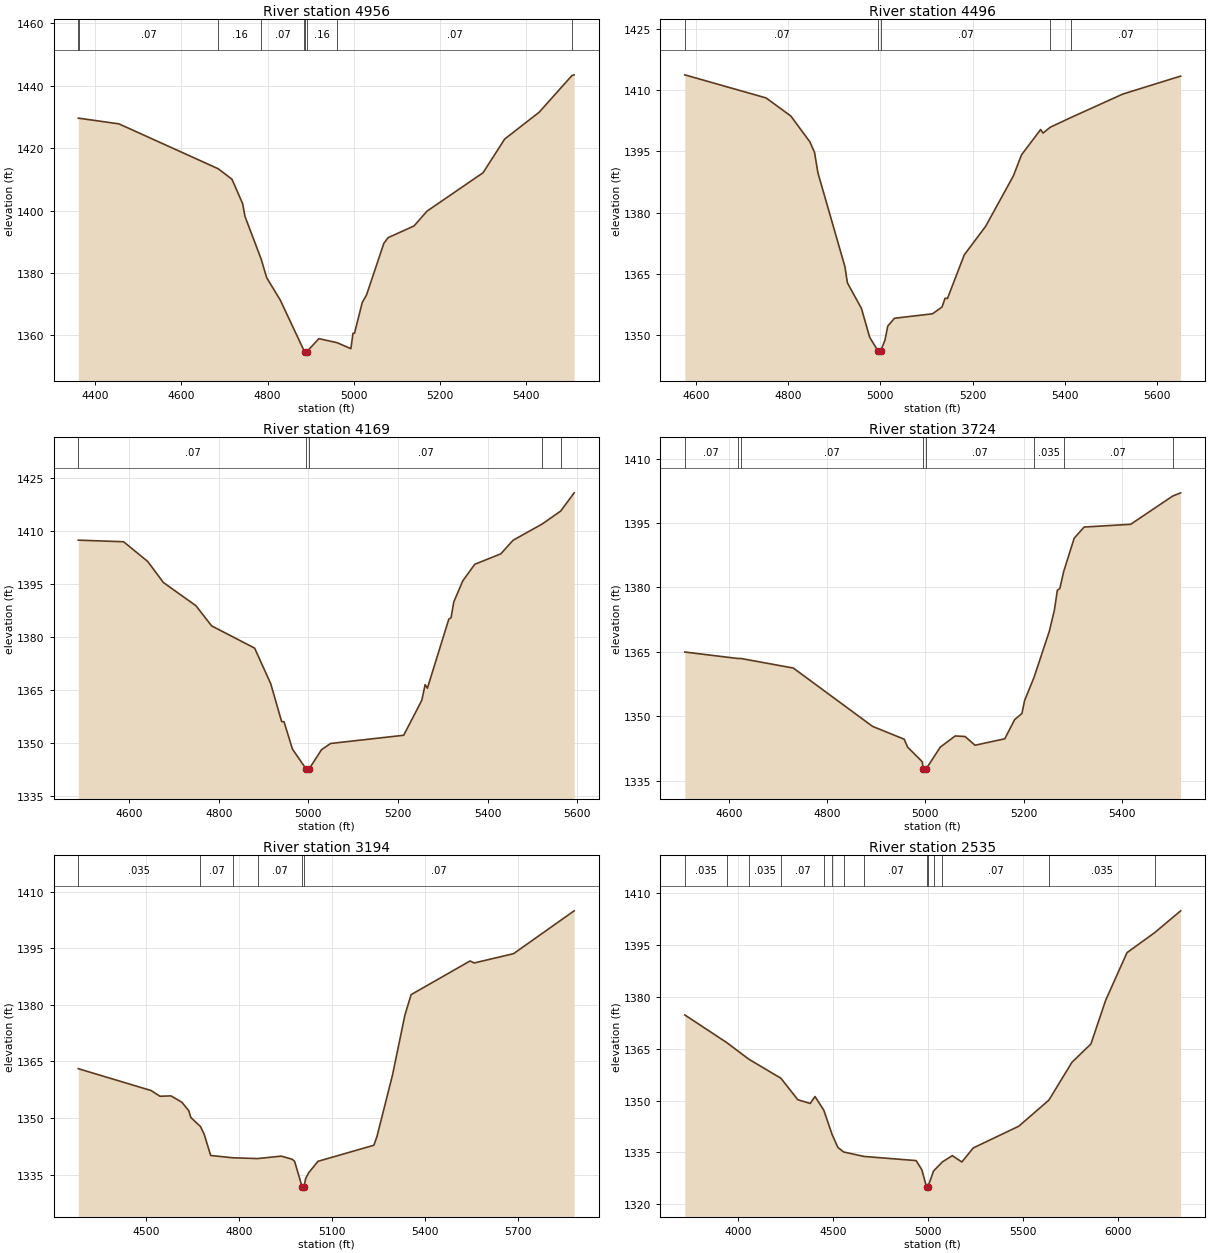
Type RM Length L Ch R = 1,4956,460,460,460
BEGIN DESCRIPTION:
Mapping XS 000eb685
END DESCRIPTION:
XS GIS Cut Line= 3
      1683488.48      7053618.66      1682853.04      7053541.84
      1682343.91      7053539.23
#Sta/Elev= 30
  4361.5 1429.56  4363.1 1429.56  4455.7 1427.75  4685.8 1413.37  4717.6 1410.01
  4742.3 1402.21  4747.8 1398.10  4785.3 1384.43  4798.1 1378.46  4829.3 1371.38
  4884.7 1355.08  4886.2 1354.82  4886.6 1354.32  4891.4 1354.82  4919.0 1358.96
  4961.1 1357.67  4993.2 1355.75  4998.1 1360.68  5001.6 1360.68  5019.6 1370.55
  5029.6 1373.00  5069.6 1389.49  5079.6 1391.31  5139.6 1395.06  5169.6 1399.79
  5299.6 1412.10  5349.6 1422.88  5429.6 1431.48  5505.5 1443.23  5510.7 1443.46
#Mann=9,-1,0
  4361.5   0.035       0  4363.1    0.07       0  4685.8    0.16       0
  4785.3    0.07       0  4884.7    0.16       0  4886.2    0.07       0
  4891.4    0.16       0  4961.1    0.07       0  5505.5   0.035       0
Bank Sta=4886.2,4891.4
Exp/Cntr=0.3,0.1

Type RM Length L Ch R = 1,4496,327,327,327
BEGIN DESCRIPTION:
Mapping XS 67416bc7
END DESCRIPTION:
XS GIS Cut Line= 3
      1683421.58      7053214.66      1683003.65      7053139.14
      1682373.43      7053295.40
#Sta/Elev= 30
  4576.3 1413.69  4752.5 1408.03  4806.0 1403.61  4847.2 1397.31  4857.4 1394.68
  4864.6 1389.74  4923.2 1366.74  4928.5 1362.81  4959.0 1356.52  4976.8 1349.48
  4995.1 1346.11  4995.6 1345.61  5000.4 1346.11  5009.9 1348.78  5016.0 1352.24
  5030.5 1354.14  5112.9 1355.23  5133.5 1356.90  5140.2 1359.05  5145.3 1358.98
  5181.6 1369.64  5228.1 1376.66  5288.1 1388.98  5305.7 1394.12  5347.1 1400.31
  5352.3 1399.44  5367.7 1400.86  5413.8 1403.30  5525.0 1408.98  5650.3 1413.38
#Mann=5,-1,0
  4576.3    0.07       0  4995.1    0.07       0  5000.4    0.07       0
  5367.7   0.035       0  5413.8    0.07       0
Bank Sta=4995.1,5000.4
Exp/Cntr=0.3,0.1

Type RM Length L Ch R = 1,4169,445,445,445
BEGIN DESCRIPTION:
Mapping XS 12cc5ad9
END DESCRIPTION:
XS GIS Cut Line= 3
      1683540.15      7053021.97      1683062.24      7052830.55
      1682480.85      7052722.84
#Sta/Elev= 30
  4486.8 1407.30  4587.8 1406.85  4641.6 1401.27  4676.6 1395.32  4749.2 1388.76
  4784.2 1383.06  4880.1 1376.77  4916.1 1366.68  4940.3 1356.02  4945.7 1355.94
  4964.5 1348.21  4995.6 1342.49  4996.0 1341.99  5001.1 1342.49  5029.3 1348.06
  5049.7 1349.81  5212.6 1352.13  5253.1 1362.03  5260.4 1366.44  5265.5 1365.44
  5313.3 1384.97  5318.4 1385.40  5324.3 1389.81  5344.6 1395.82  5371.2 1400.48
  5429.2 1403.42  5456.5 1407.25  5521.9 1411.89  5563.0 1415.54  5592.9 1420.68
#Mann=5,-1,0
  4486.8    0.07       0  4995.6    0.07       0  5001.1    0.07       0
  5521.9   0.035       0  5563.0    0.07       0
Bank Sta=4995.6,5001.1
Exp/Cntr=0.3,0.1

Type RM Length L Ch R = 1,3724,530,530,530
BEGIN DESCRIPTION:
Mapping XS 316b63cf
END DESCRIPTION:
XS GIS Cut Line= 3
      1683560.59      7052578.99      1683102.26      7052399.30
      1682590.56      7052328.99
#Sta/Elev= 30
  4510.7 1364.96  4618.1 1363.46  4625.2 1363.45  4731.5 1361.23  4892.6 1347.65
  4957.1 1344.65  4964.0 1342.82  4993.8 1339.41  4996.1 1337.72  4996.5 1337.22
  5001.6 1337.72  5030.5 1342.81  5060.8 1345.41  5081.0 1345.28  5101.2 1343.25
  5161.7 1344.75  5181.9 1349.24  5196.6 1350.64  5202.1 1353.68  5221.1 1359.01
  5252.6 1369.88  5262.7 1374.74  5268.7 1379.35  5273.7 1379.74  5281.7 1383.76
  5303.0 1391.48  5323.2 1394.07  5417.9 1394.71  5503.2 1401.28  5519.5 1402.04
#Mann=8,-1,0
  4510.7    0.07       0  4618.1   0.035       0  4625.2    0.07       0
  4996.1    0.07       0  5001.6    0.07       0  5221.1   0.035       0
  5281.7    0.07       0  5503.2   0.035       0
Bank Sta=4996.1,5001.6
Exp/Cntr=0.3,0.1

Type RM Length L Ch R = 1,3194,659,659,659
BEGIN DESCRIPTION:
Mapping XS c6732d8b
END DESCRIPTION:
XS GIS Cut Line= 3
      1683705.40      7052547.37      1683258.35      7051983.13
      1682379.72      7051935.41
#Sta/Elev= 30
  4281.5 1363.07  4516.2 1357.28  4545.0 1355.76  4580.3 1355.86  4615.5 1354.19
  4637.9 1351.92  4644.4 1350.14  4675.6 1347.73  4687.7 1345.65  4708.5 1340.06
  4779.9 1339.45  4859.7 1339.24  4936.0 1339.89  4971.3 1339.07  4979.3 1338.50
  5004.0 1331.64  5004.4 1331.14  5009.6 1331.64  5014.7 1333.91  5024.8 1335.48
  5054.8 1338.52  5235.1 1342.77  5245.1 1345.09  5295.2 1361.41  5335.2 1377.27
  5355.2 1382.70  5545.5 1391.63  5558.7 1391.10  5685.7 1393.56  5881.3 1404.92
#Mann=6,-1,0
  4281.5   0.035       0  4675.6    0.07       0  4779.9   0.035       0
  4859.7    0.07       0  5004.0    0.07       0  5009.6    0.07       0
Bank Sta=5004,5009.6
Exp/Cntr=0.3,0.1

Type RM Length L Ch R = 1,2535,0,0,0
BEGIN DESCRIPTION:
Mapping XS 70391579
END DESCRIPTION:
XS GIS Cut Line= 3
      1683859.48      7052840.30      1683724.80      7051567.51
      1682392.45      7051546.94
#Sta/Elev= 30
  3720.1 1374.80  3941.5 1366.78  4057.2 1362.00  4226.8 1356.46  4315.7 1350.25
  4380.7 1349.17  4406.2 1351.18  4452.6 1347.21  4496.5 1340.15  4526.9 1336.43
  4557.4 1335.12  4664.6 1333.83  4939.2 1332.63  4969.3 1329.94  4994.4 1324.87
  4994.9 1324.37  5000.1 1324.87  5030.7 1329.62  5077.6 1332.27  5129.8 1334.06
  5179.8 1332.23  5239.8 1336.29  5479.9 1342.59  5638.1 1350.12  5759.9 1361.09
  5859.9 1366.40  5937.3 1379.01  6049.9 1392.83  6195.7 1398.62  6332.5 1404.94
#Mann=14,-1,0
  3720.1   0.035       0  3941.5    0.07       0  4057.2   0.035       0
  4226.8    0.07       0  4452.6   0.035       0  4496.5    0.07       0
  4557.4   0.035       0  4664.6    0.07       0  4994.4    0.07       0
  5000.1    0.07       0  5030.7    0.16       0  5077.6    0.07       0
  5638.1   0.035       0  6195.7    0.07       0
Bank Sta=4994.4,5000.1
Exp/Cntr=0.3,0.1

Chan Stop Cuts=-1