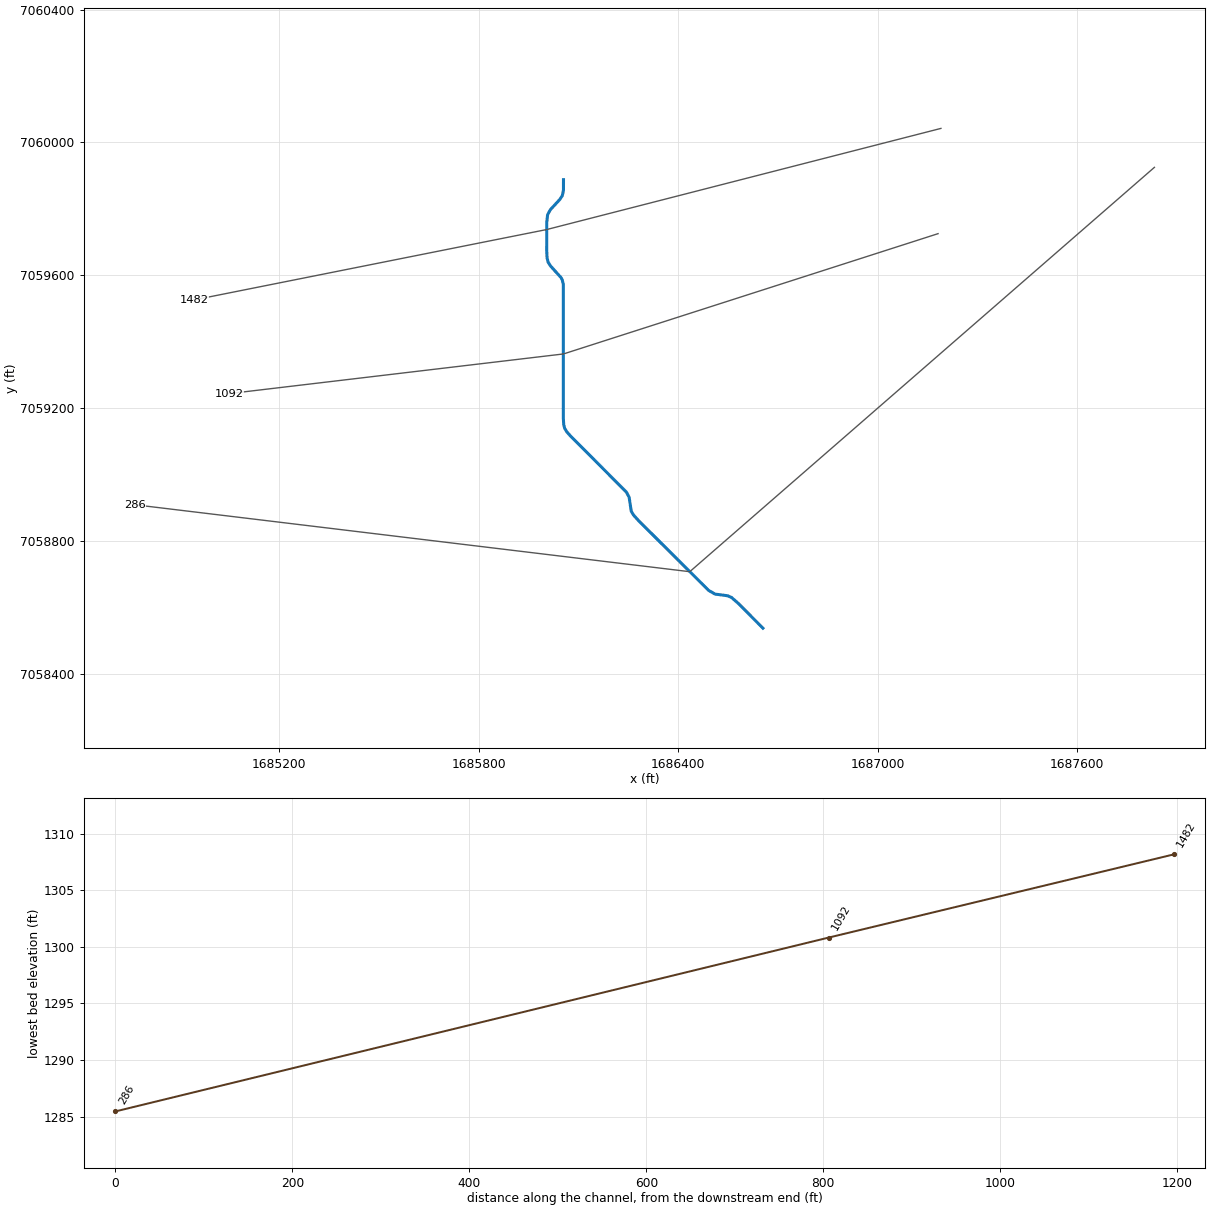
--- Chimney Creek 1195.prj (project) ---

Proj Title=Chimney Creek 1195 Base Level Engineering
Current Plan=p01
Default Exp/Contr=0.3,0.1
English Units
Geom File=g01
Flow File=f01
Plan File=p01
BEGIN DESCRIPTION:
Chimney Creek 1195
END DESCRIPTION:

--- Chimney Creek 1195.p01 (plan) ---

Plan Title=Multiple Run
Short Identifier=Multiple
Geom File=g01
Flow File=f01
Subcritical Flow
K Sum by GR= 0
Std Step Tol= 0.01
Critical Tol= 0.01
Num of Std Step Trials= 20
Max Error Tol= 0.3
Flow Tol Ratio= 0.001
Split Flow NTrial= 30
Split Flow Tol= 0.02
Split Flow Ratio= 0.02
Log Output Level= 0
Friction Slope Method= 1
Unsteady Friction Slope Method= 2
Unsteady Bridges Friction Slope Method= 1
Parabolic Critical Depth
Global Vel Dist=  1 , 1 , 1
Global Log Level= 0
CheckData=True
Encroach Param= -1, 0, 0, 0
BEGIN DESCRIPTION:
Multiple Run
END DESCRIPTION:

--- Chimney Creek 1195.f01 (steady flow) ---

Flow Title=Multiple
Number of Profiles=7
Profile Names=10-year,25-year,50-year,1pct_min,100-year,1pct_plu,500-year
River Rch & RM= Chimney Creek 11,Reach-1,1482
     740    1103    1426     917    1829    3650    3038
Boundary for River Rch & Prof#=Chimney Creek 11,Reach-1,1
Up Type=0
Dn Type=3
Dn Slope=0.005
Boundary for River Rch & Prof#=Chimney Creek 11,Reach-1,2
Up Type=0
Dn Type=3
Dn Slope=0.005
Boundary for River Rch & Prof#=Chimney Creek 11,Reach-1,3
Up Type=0
Dn Type=3
Dn Slope=0.005
Boundary for River Rch & Prof#=Chimney Creek 11,Reach-1,4
Up Type=0
Dn Type=3
Dn Slope=0.005
Boundary for River Rch & Prof#=Chimney Creek 11,Reach-1,5
Up Type=0
Dn Type=3
Dn Slope=0.005
Boundary for River Rch & Prof#=Chimney Creek 11,Reach-1,6
Up Type=0
Dn Type=3
Dn Slope=0.005
Boundary for River Rch & Prof#=Chimney Creek 11,Reach-1,7
Up Type=0
Dn Type=3
Dn Slope=0.005

--- Chimney Creek 1195.g01 (geometry) ---

Geom Title=Existing Conditions

River Reach=Chimney Creek 11,Reach-1
Reach XY= 30
      1686055.00      7059888.00      1686054.88      7059856.20
      1686051.35      7059839.51      1686043.94      7059828.44
      1686015.56      7059797.76      1686007.11      7059782.12
      1686004.59      7059758.14      1686004.52      7059674.20
      1686005.67      7059651.93      1686008.77      7059639.57
      1686015.85      7059628.35      1686046.86      7059594.06
      1686051.22      7059586.43      1686054.48      7059572.78
      1686054.54      7059169.63      1686055.54      7059151.86
      1686058.54      7059139.46      1686065.48      7059128.20
      1686077.86      7059114.47      1686244.22      7058947.68
      1686252.47      7058931.95      1686258.98      7058889.65
      1686265.78      7058878.32      1686281.30      7058861.18
      1686491.79      7058651.63      1686511.04      7058640.52
      1686548.96      7058635.48      1686561.07      7058629.89
      1686581.86      7058611.80      1686655.00      7058538.00

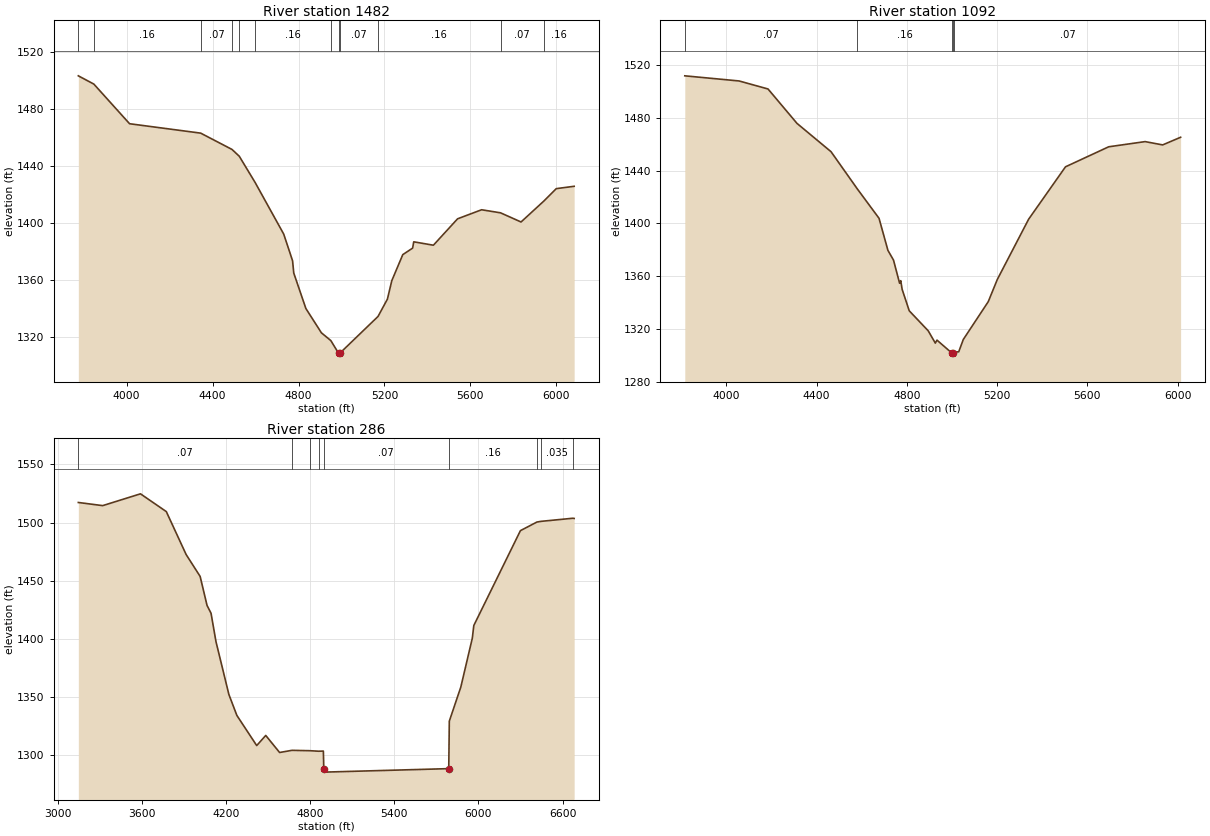
Type RM Length L Ch R = 1,1482,390,390,390
BEGIN DESCRIPTION:
Chimney Creek 1195 3.0
END DESCRIPTION:
XS GIS Cut Line= 3
      1687190.78      7060042.33      1686005.00      7059738.00
      1684942.59      7059525.85
#Sta/Elev= 30
  3775.3 1503.59  3847.5 1497.79  4013.8 1469.95  4344.7 1463.35  4490.5 1451.90
  4524.3 1447.13  4597.9 1428.76  4731.1 1392.48  4772.4 1373.72  4777.9 1365.12
  4834.3 1340.21  4906.6 1323.14  4950.5 1317.68  4986.9 1308.67  4987.2 1308.17
  4991.5 1308.67  5170.0 1334.61  5213.7 1346.76  5234.2 1359.73  5285.3 1378.03
  5331.2 1382.62  5336.3 1387.04  5427.8 1384.65  5540.4 1403.19  5652.1 1409.54
  5740.3 1407.39  5835.7 1400.96  5941.2 1415.56  5999.6 1424.37  6082.9 1426.03
#Mann=12,-1,0
  3775.3    0.07       0  3847.5    0.16       0  4344.7    0.07       0
  4490.5    0.16       0  4524.3    0.07       0  4597.9    0.16       0
  4950.5    0.07       0  4986.9    0.07       0  4991.5    0.07       0
  5170.0    0.16       0  5740.3    0.07       0  5941.2    0.16       0
Bank Sta=4986.9,4991.5
Exp/Cntr=0.3,0.1

Type RM Length L Ch R = 1,1092,806,806,806
BEGIN DESCRIPTION:
Chimney Creek 1195 2.0
END DESCRIPTION:
XS GIS Cut Line= 3
      1687182.17      7059725.51      1686055.01      7059363.40
      1685048.37      7059243.92
#Sta/Elev= 30
  3816.1 1511.80  4056.6 1507.91  4185.0 1501.83  4313.4 1475.74  4464.3 1454.28
  4581.1 1426.00  4677.0 1403.79  4716.4 1379.48  4741.2 1372.10  4768.1 1354.57
  4773.3 1356.52  4779.4 1349.93  4810.9 1333.67  4895.0 1318.50  4926.5 1309.17
  4933.8 1311.44  5001.9 1301.32  5002.3 1300.82  5006.5 1301.32  5011.1 1302.43
  5030.2 1302.57  5050.4 1311.90  5161.1 1340.59  5201.4 1357.48  5340.1 1403.11
  5503.5 1442.83  5694.9 1458.00  5856.4 1461.93  5934.1 1459.43  6013.7 1465.22
#Mann=5,-1,0
  3816.1    0.07       0  4581.1    0.16       0  5001.9    0.07       0
  5006.5    0.16       0  5011.1    0.07       0
Bank Sta=5001.9,5006.5
Exp/Cntr=0.3,0.1

Type RM Length L Ch R = 1,286,0,0,0
BEGIN DESCRIPTION:
Chimney Creek 1195 1.0
END DESCRIPTION:
XS GIS Cut Line= 3
      1687833.17      7059925.14      1686434.97      7058707.93
      1684764.59      7058909.52
#Sta/Elev= 30
  3146.2 1517.32  3319.9 1514.61  3589.5 1524.76  3773.7 1509.48  3915.2 1472.54
  4014.9 1453.77  4064.2 1428.81  4092.7 1422.09  4127.9 1397.68  4219.9 1352.27
  4276.9 1334.23  4418.4 1308.30  4482.9 1317.01  4581.7 1302.35  4669.7 1304.20
  4798.0 1303.88  4859.6 1303.44  4893.9 1303.55  4896.8 1288.46  4899.9 1285.46
  5788.1 1288.46  5792.1 1329.31  5874.1 1358.58  5956.1 1400.61  5966.9 1411.56
  6299.3 1493.11  6416.6 1500.47  6444.3 1501.07  6672.9 1503.76  6682.5 1503.58
#Mann=9,-1,0
  3146.2    0.07       0  4669.7    0.07       0  4798.0   0.035       0
  4859.6    0.07       0  4896.8    0.07       0  5788.1    0.16       0
  6416.6    0.07       0  6444.3   0.035       0  6672.9    0.07       0
Bank Sta=4896.8,5788.1
Exp/Cntr=0.3,0.1

Chan Stop Cuts=-1