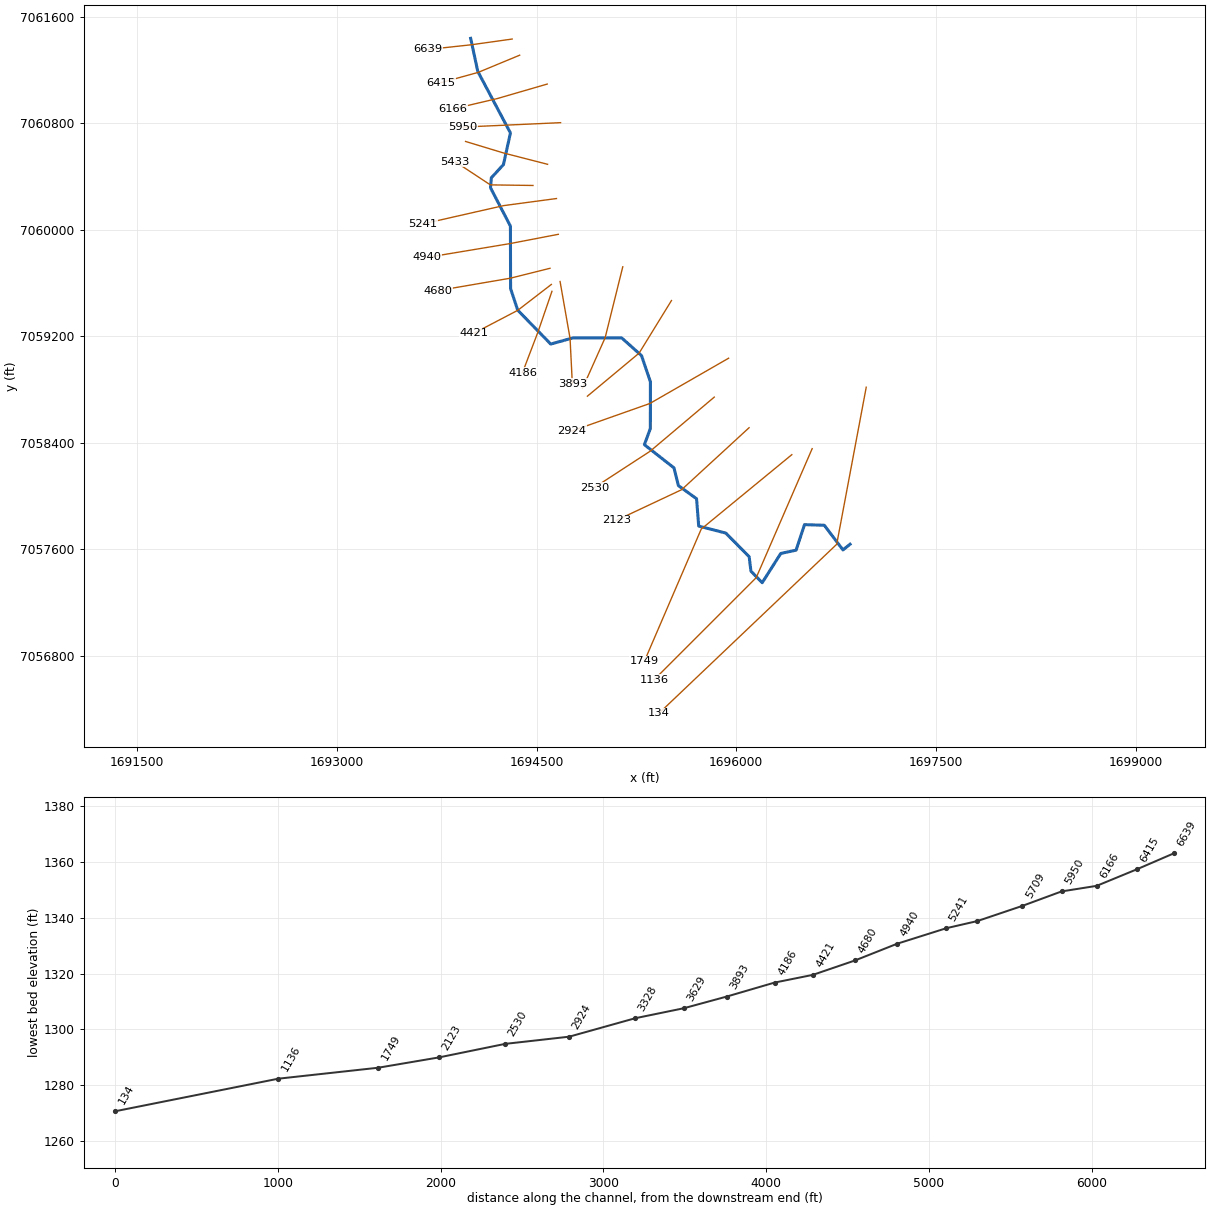
--- Chimney Creek 1196.prj (project) ---

Proj Title=Chimney Creek 1196 Base Level Engineering
Current Plan=p01
Default Exp/Contr=0.3,0.1
English Units
Geom File=g01
Flow File=f01
Plan File=p01
BEGIN DESCRIPTION:
Chimney Creek 1196
END DESCRIPTION:

--- Chimney Creek 1196.p01 (plan) ---

Plan Title=Multiple Run
Short Identifier=Multiple
Geom File=g01
Flow File=f01
Subcritical Flow
K Sum by GR= 0
Std Step Tol= 0.01
Critical Tol= 0.01
Num of Std Step Trials= 20
Max Error Tol= 0.3
Flow Tol Ratio= 0.001
Split Flow NTrial= 30
Split Flow Tol= 0.02
Split Flow Ratio= 0.02
Log Output Level= 0
Friction Slope Method= 1
Unsteady Friction Slope Method= 2
Unsteady Bridges Friction Slope Method= 1
Parabolic Critical Depth
Global Vel Dist=  1 , 1 , 1
Global Log Level= 0
CheckData=True
Encroach Param= -1, 0, 0, 0
BEGIN DESCRIPTION:
Multiple Run
END DESCRIPTION:

--- Chimney Creek 1196.f01 (steady flow) ---

Flow Title=Multiple
Number of Profiles=7
Profile Names=10-year,25-year,50-year,1pct_min,100-year,1pct_plu,500-year
River Rch & RM= Chimney Creek 11,Reach-1,6639
     448     640     804     502    1002    1999    1569
River Rch & RM= Chimney Creek 11,Reach-1,4940
     783    1155    1481     943    1882    3754    3065
Boundary for River Rch & Prof#=Chimney Creek 11,Reach-1,1
Up Type=0
Dn Type=3
Dn Slope=0.005
Boundary for River Rch & Prof#=Chimney Creek 11,Reach-1,2
Up Type=0
Dn Type=3
Dn Slope=0.005
Boundary for River Rch & Prof#=Chimney Creek 11,Reach-1,3
Up Type=0
Dn Type=3
Dn Slope=0.005
Boundary for River Rch & Prof#=Chimney Creek 11,Reach-1,4
Up Type=0
Dn Type=3
Dn Slope=0.005
Boundary for River Rch & Prof#=Chimney Creek 11,Reach-1,5
Up Type=0
Dn Type=3
Dn Slope=0.005
Boundary for River Rch & Prof#=Chimney Creek 11,Reach-1,6
Up Type=0
Dn Type=3
Dn Slope=0.005
Boundary for River Rch & Prof#=Chimney Creek 11,Reach-1,7
Up Type=0
Dn Type=3
Dn Slope=0.005

--- Chimney Creek 1196.g01 (geometry) ---

Geom Title=Existing Conditions

River Reach=Chimney Creek 11,Reach-1
Reach XY= 30
      1694005.00      7061438.00      1694058.76      7061189.56
      1694303.91      7060727.46      1694251.38      7060489.50
      1694160.41      7060390.42      1694154.41      7060315.22
      1694303.78      7060027.50      1694305.07      7059558.03
      1694358.66      7059396.19      1694606.50      7059141.46
      1694773.27      7059187.79      1695139.84      7059187.62
      1695288.54      7059054.76      1695355.36      7058858.15
      1695354.77      7058506.26      1695310.08      7058385.69
      1695532.14      7058211.57      1695565.51      7058078.19
      1695701.93      7057979.70      1695718.20      7057774.26
      1695921.76      7057721.57      1696097.14      7057544.17
      1696110.52      7057435.54      1696195.11      7057348.89
      1696334.48      7057568.53      1696449.56      7057593.25
      1696512.97      7057785.08      1696661.47      7057780.31
      1696801.65      7057595.24      1696855.00      7057638.00

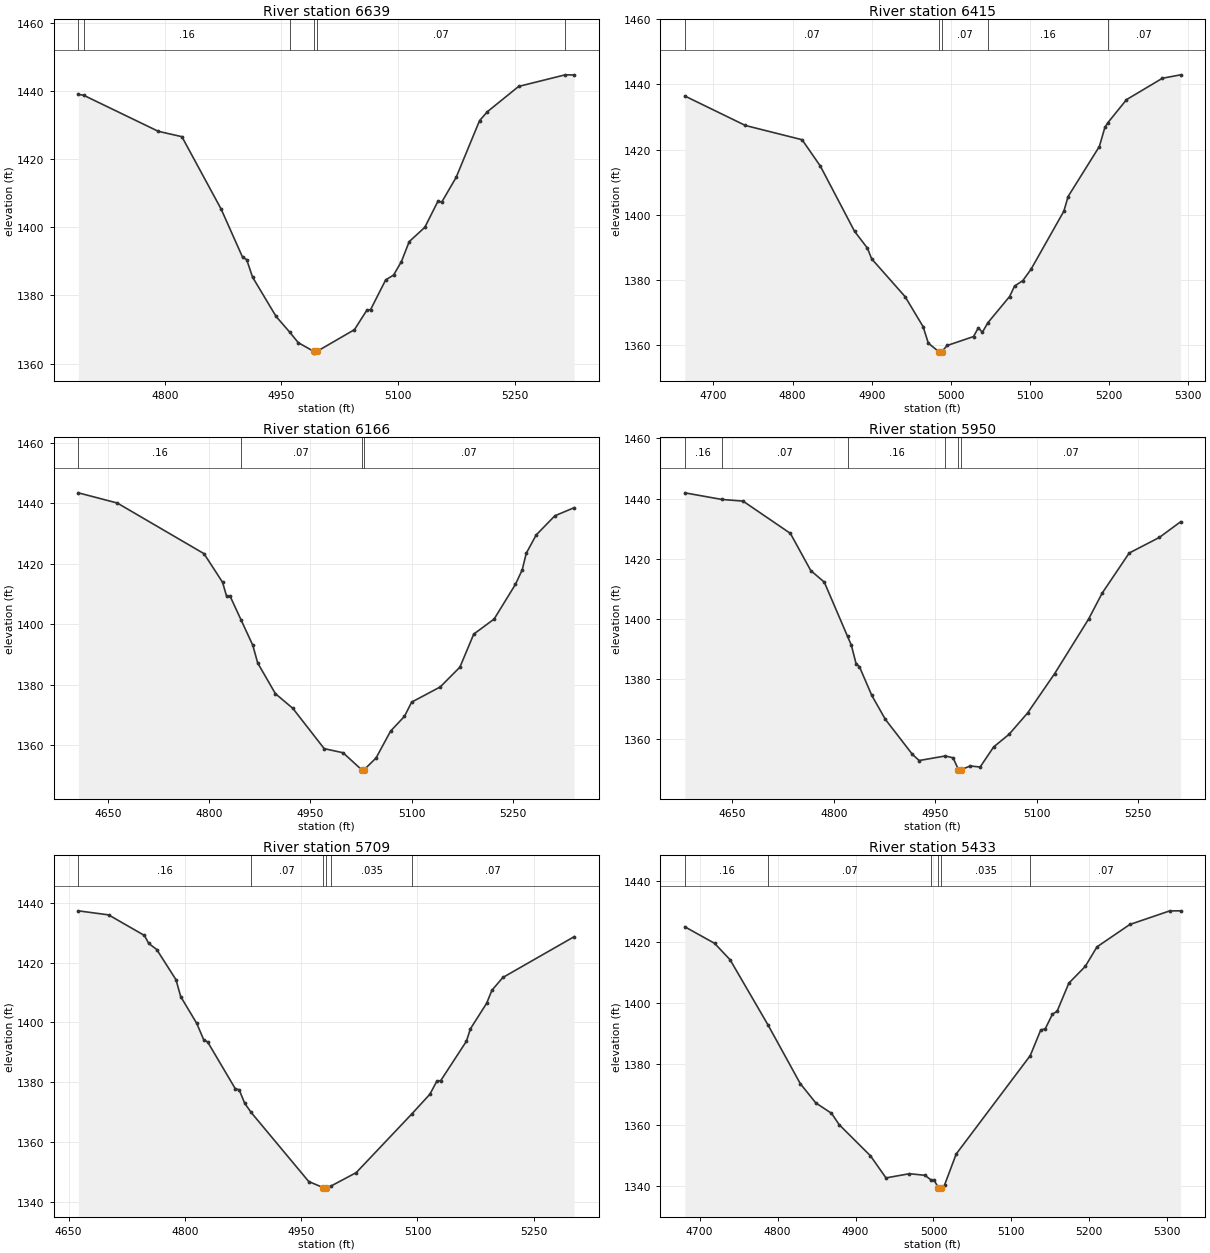
Type RM Length L Ch R = 1,6639,224,224,224
BEGIN DESCRIPTION:
Chimney Creek 1196 14.0
END DESCRIPTION:
XS GIS Cut Line= 3
      1694316.94      7061432.64      1694008.65      7061389.51
      1693684.05      7061354.27
#Sta/Elev= 30
  4688.7 1438.98  4695.6 1438.70  4791.6 1428.13  4821.9 1426.56  4872.4 1405.32
  4900.1 1391.14  4905.2 1390.53  4912.8 1385.37  4943.1 1373.82  4960.4 1369.28
  4971.6 1366.14  4991.6 1363.57  4991.8 1363.07  4995.6 1363.57  5043.9 1369.96
  5059.7 1375.62  5064.7 1375.86  5084.1 1384.57  5094.2 1385.96  5104.3 1389.93
  5114.3 1395.77  5134.4 1399.98  5151.2 1407.58  5156.3 1407.42  5174.7 1414.63
  5204.8 1431.26  5214.9 1433.89  5255.1 1441.30  5315.0 1444.70  5326.5 1444.66
#Mann=6,-1,0
  4688.7    0.07       0  4695.6    0.16       0  4960.4    0.07       0
  4991.6    0.07       0  4995.6    0.07       0  5315.0   0.035       0
Bank Sta=4991.6,4995.6
Exp/Cntr=0.3,0.1

Type RM Length L Ch R = 1,6415,249,249,249
BEGIN DESCRIPTION:
Mapping XS 706dca6b
END DESCRIPTION:
XS GIS Cut Line= 3
      1694373.14      7061311.33      1694061.71      7061182.20
      1693782.79      7061105.15
#Sta/Elev= 30
  4663.9 1436.47  4740.5 1427.40  4812.1 1423.02  4835.1 1414.95  4878.4 1394.87
  4894.6 1389.72  4900.0 1386.42  4942.3 1374.78  4965.0 1365.57  4971.6 1360.50
  4984.6 1357.93  4984.9 1357.43  4988.6 1357.93  4995.5 1359.78  5028.7 1362.52
  5034.8 1365.21  5039.9 1363.84  5046.9 1366.79  5074.3 1374.83  5080.6 1378.04
  5091.0 1379.72  5101.4 1383.22  5142.9 1401.08  5148.2 1405.56  5187.7 1420.94
  5194.7 1426.81  5198.4 1428.24  5222.0 1435.34  5267.4 1441.92  5290.4 1442.97
#Mann=5,-1,0
  4663.9    0.07       0  4984.6    0.07       0  4988.6    0.07       0
  5046.9    0.16       0  5198.4    0.07       0
Bank Sta=4984.6,4988.6
Exp/Cntr=0.3,0.1

Type RM Length L Ch R = 1,6166,216,216,216
BEGIN DESCRIPTION:
Mapping XS ec1e8c16
END DESCRIPTION:
XS GIS Cut Line= 3
      1694580.27      7061094.47      1694203.49      7060985.08
      1693870.16      7060906.96
#Sta/Elev= 30
  4606.1 1443.41  4663.7 1440.05  4792.3 1423.31  4819.8 1413.86  4825.8 1409.23
  4831.0 1409.25  4847.1 1401.48  4864.6 1393.05  4871.9 1387.17  4898.1 1377.05
  4924.0 1372.18  4970.4 1358.88  4998.4 1357.52  5025.7 1351.95  5025.9 1351.45
  5029.7 1351.95  5047.2 1355.78  5068.8 1364.68  5089.3 1369.54  5100.0 1374.25
  5142.4 1379.28  5171.5 1385.81  5192.0 1396.73  5222.2 1401.70  5253.7 1413.13
  5263.9 1418.01  5269.8 1423.43  5284.5 1429.48  5312.2 1435.82  5340.8 1438.50
#Mann=4,-1,0
  4606.1    0.16       0  4847.1    0.07       0  5025.7    0.07       0
  5029.7    0.07       0
Bank Sta=5025.7,5029.7
Exp/Cntr=0.3,0.1

Type RM Length L Ch R = 1,5950,241,241,241
BEGIN DESCRIPTION:
Mapping XS 9e424896
END DESCRIPTION:
XS GIS Cut Line= 3
      1694680.87      7060804.52      1694259.04      7060785.43
      1693949.11      7060771.57
#Sta/Elev= 30
  4580.0 1441.89  4634.4 1439.70  4666.0 1439.14  4736.0 1428.41  4766.1 1416.07
  4786.1 1412.23  4820.5 1394.18  4826.1 1391.24  4833.0 1385.18  4838.0 1384.14
  4856.2 1374.62  4876.2 1366.68  4916.2 1355.03  4926.2 1352.97  4964.7 1354.48
  4976.3 1353.88  4984.3 1349.95  4984.5 1349.45  4988.3 1349.95  5001.8 1351.17
  5016.3 1350.81  5036.3 1357.49  5059.0 1361.67  5086.4 1368.76  5126.4 1381.84
  5176.5 1399.94  5196.5 1408.54  5236.5 1421.89  5281.1 1427.08  5312.5 1432.28
#Mann=6,-1,0
  4580.0    0.16       0  4634.4    0.07       0  4820.5    0.16       0
  4964.7    0.07       0  4984.3    0.07       0  4988.3    0.07       0
Bank Sta=4984.3,4988.3
Exp/Cntr=0.3,0.1

Type RM Length L Ch R = 1,5709,276,276,276
BEGIN DESCRIPTION:
Mapping XS 4d6d20f7
END DESCRIPTION:
XS GIS Cut Line= 3
      1694582.89      7060491.86      1694253.49      7060576.49
      1693966.97      7060663.35
#Sta/Elev= 30
  4662.6 1437.27  4701.7 1435.91  4747.9 1429.03  4753.3 1426.40  4763.7 1424.34
  4788.6 1414.23  4794.6 1408.62  4815.3 1399.67  4824.2 1394.25  4829.4 1393.44
  4864.9 1377.89  4870.1 1377.45  4877.2 1372.95  4885.5 1369.90  4959.8 1346.80
  4978.5 1344.77  4978.7 1344.27  4982.5 1344.77  4988.7 1345.34  5021.0 1349.78
  5092.9 1369.45  5116.1 1376.01  5124.9 1380.31  5130.1 1380.57  5163.1 1393.68
  5168.3 1397.85  5189.2 1406.37  5196.0 1410.71  5210.1 1414.99  5302.1 1428.63
#Mann=6,-1,0
  4662.6    0.16       0  4885.5    0.07       0  4978.5   0.035       0
  4982.5    0.07       0  4988.7   0.035       0  5092.9    0.07       0
Bank Sta=4978.5,4982.5
Exp/Cntr=0.3,0.1

Type RM Length L Ch R = 1,5433,192,192,192
BEGIN DESCRIPTION:
Mapping XS afa2330a
END DESCRIPTION:
XS GIS Cut Line= 3
      1694473.22      7060332.83      1694153.17      7060337.17
      1693889.23      7060511.33
#Sta/Elev= 30
  4680.9 1425.09  4719.1 1419.65  4739.1 1414.22  4787.9 1392.72  4829.1 1373.52
  4849.1 1367.16  4869.1 1363.79  4879.1 1360.01  4919.1 1349.81  4939.1 1342.53
  4969.2 1343.91  4989.2 1343.38  4997.4 1341.75  5001.0 1341.71  5006.2 1339.34
  5006.4 1338.84  5010.2 1339.34  5014.2 1340.16  5029.2 1350.39  5124.2 1382.73
  5137.6 1391.10  5143.6 1391.62  5152.7 1396.36  5158.7 1397.31  5173.7 1406.54
  5194.8 1412.06  5209.9 1418.49  5252.0 1425.84  5303.2 1430.31  5317.2 1430.33
#Mann=6,-1,0
  4680.9    0.16       0  4787.9    0.07       0  4997.4   0.035       0
  5006.2   0.035       0  5010.2   0.035       0  5124.2    0.07       0
Bank Sta=5006.2,5010.2
Exp/Cntr=0.3,0.1

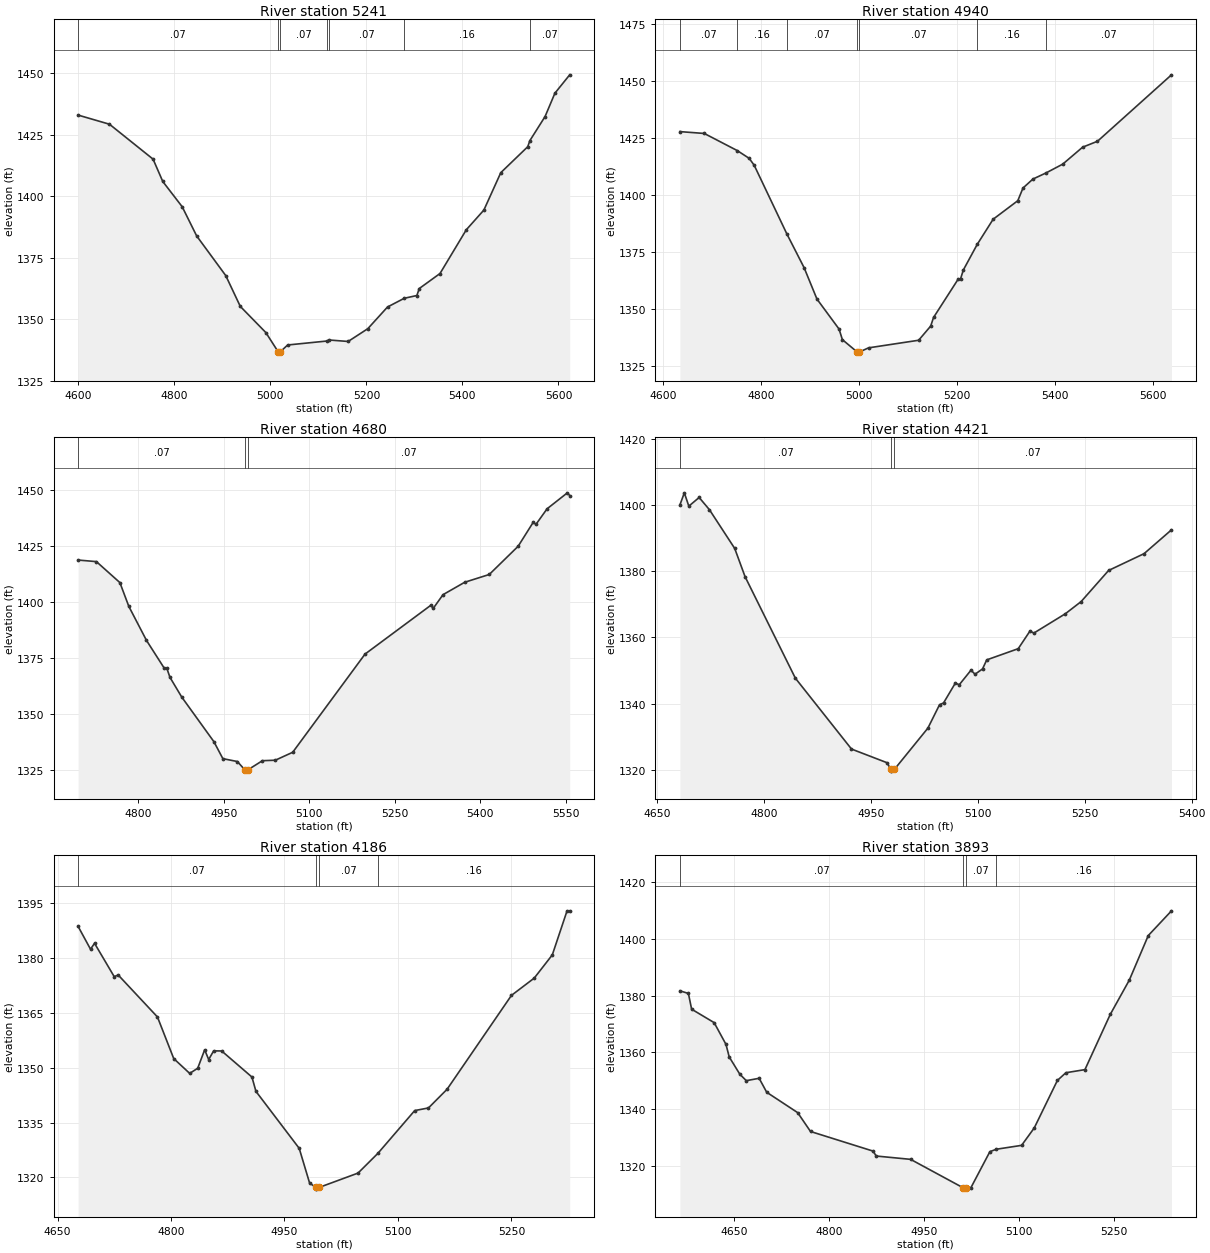
Type RM Length L Ch R = 1,5241,301,301,301
BEGIN DESCRIPTION:
Mapping XS b80ada4b
END DESCRIPTION:
XS GIS Cut Line= 3
      1694649.74      7060234.59      1694252.64      7060181.43
      1693645.01      7060043.63
#Sta/Elev= 30
  4599.7 1433.02  4665.0 1429.31  4755.8 1415.11  4776.0 1406.03  4816.4 1395.77
  4846.6 1383.89  4907.2 1367.76  4937.4 1355.26  4990.7 1344.61  5016.4 1336.76
  5016.7 1336.26  5020.4 1336.76  5036.1 1339.57  5117.9 1341.18  5123.0 1341.59
  5162.0 1341.00  5203.0 1346.20  5244.0 1355.01  5278.9 1358.56  5305.1 1359.68
  5310.2 1362.53  5353.3 1368.62  5408.1 1386.41  5444.7 1394.42  5479.9 1409.62
  5536.0 1420.16  5540.5 1422.66  5572.1 1432.43  5592.6 1441.93  5623.4 1449.39
#Mann=7,-1,0
  4599.7    0.07       0  5016.4    0.07       0  5020.4    0.07       0
  5117.9   0.035       0  5123.0    0.07       0  5278.9    0.16       0
  5540.5    0.07       0
Bank Sta=5016.4,5020.4
Exp/Cntr=0.3,0.1

Type RM Length L Ch R = 1,4940,260,260,260
BEGIN DESCRIPTION:
Mapping XS 25a3737b
END DESCRIPTION:
XS GIS Cut Line= 3
      1694663.85      7059965.93      1694302.77      7059896.49
      1693676.06      7059792.33
#Sta/Elev= 30
  4634.6 1427.74  4684.3 1426.93  4751.7 1419.42  4776.0 1416.02  4786.2 1412.99
  4852.8 1382.93  4888.0 1368.14  4914.2 1354.40  4959.3 1341.26  4966.1 1336.62
  4996.3 1331.22  4996.6 1330.72  5000.9 1331.22  5019.4 1333.03  5121.7 1336.36
  5146.3 1342.58  5152.1 1346.34  5202.1 1363.04  5207.2 1363.23  5212.9 1367.14
  5241.3 1378.38  5273.7 1389.36  5324.0 1397.48  5334.6 1403.03  5354.8 1406.95
  5381.9 1409.67  5415.7 1413.50  5456.2 1420.91  5486.6 1423.51  5637.6 1452.61
#Mann=7,-1,0
  4634.6    0.07       0  4751.7    0.16       0  4852.8    0.07       0
  4996.3    0.07       0  5000.9    0.07       0  5241.3    0.16       0
  5381.9    0.07       0
Bank Sta=4996.3,5000.9
Exp/Cntr=0.3,0.1

Type RM Length L Ch R = 1,4680,259,259,259
BEGIN DESCRIPTION:
Mapping XS 3062aa58
END DESCRIPTION:
XS GIS Cut Line= 3
      1694601.38      7059710.73      1694302.77      7059636.07
      1693755.85      7059542.32
#Sta/Elev= 30
  4694.4 1418.66  4726.5 1417.96  4767.7 1408.62  4783.4 1398.02  4814.4 1382.89
  4845.0 1370.74  4850.2 1370.39  4855.6 1366.44  4876.2 1357.69  4932.7 1337.81
  4948.4 1330.27  4973.9 1328.98  4987.2 1325.21  4987.6 1324.71  4991.9 1325.21
  5017.8 1329.35  5040.5 1329.57  5071.0 1333.10  5197.9 1376.80  5312.9 1398.44
  5317.9 1397.26  5334.8 1403.25  5372.9 1408.78  5415.9 1412.23  5466.6 1424.79
  5492.9 1435.39  5498.0 1434.58  5517.4 1441.47  5553.0 1448.58  5557.1 1447.37
#Mann=3,-1,0
  4694.4    0.07       0  4987.2    0.07       0  4991.9    0.07       0
Bank Sta=4987.2,4991.9
Exp/Cntr=0.3,0.1

Type RM Length L Ch R = 1,4421,235,235,235
BEGIN DESCRIPTION:
Mapping XS cb983956
END DESCRIPTION:
XS GIS Cut Line= 3
      1694611.35      7059589.55      1694359.63      7059395.33
      1694030.03      7059222.95
#Sta/Elev= 30
  4681.8 1400.12  4688.0 1403.78  4694.3 1399.75  4708.8 1402.37  4723.3 1398.65
  4758.7 1386.95  4773.2 1378.42  4843.8 1347.69  4922.6 1326.23  4972.4 1322.10
  4978.0 1320.05  4978.3 1319.55  4982.7 1320.05  5029.8 1332.56  5046.2 1339.66
  5051.8 1340.19  5068.3 1346.18  5073.9 1345.71  5090.3 1350.10  5096.0 1348.88
  5106.5 1350.48  5112.4 1353.22  5156.6 1356.61  5173.0 1361.92  5178.6 1361.34
  5222.8 1367.19  5244.9 1370.87  5283.4 1380.28  5333.2 1385.37  5371.7 1392.58
#Mann=3,-1,0
  4681.8    0.07       0  4978.0    0.07       0  4982.7    0.07       0
Bank Sta=4978,4982.7
Exp/Cntr=0.3,0.1

Type RM Length L Ch R = 1,4186,293,293,293
BEGIN DESCRIPTION:
Mapping XS 2f14ac7f
END DESCRIPTION:
XS GIS Cut Line= 3
      1694615.71      7059537.49      1694510.45      7059231.49
      1694394.33      7058926.55
#Sta/Elev= 30
  4677.2 1388.63  4693.6 1382.39  4698.9 1384.01  4724.9 1374.90  4730.2 1375.34
  4782.1 1363.86  4803.6 1352.49  4824.7 1348.44  4835.3 1349.84  4844.5 1354.89
  4849.8 1352.23  4856.4 1354.60  4867.0 1354.57  4907.0 1347.44  4912.3 1343.52
  4969.5 1327.94  4983.3 1318.41  4991.6 1317.29  4991.9 1316.79  4996.3 1317.29
  5047.3 1321.18  5073.6 1326.59  5122.2 1338.27  5140.4 1338.99  5165.0 1344.10
  5250.1 1369.77  5280.2 1374.49  5304.1 1380.84  5323.6 1392.89  5327.1 1392.89
#Mann=4,-1,0
  4677.2    0.07       0  4991.6    0.07       0  4996.3    0.07       0
  5073.6    0.16       0
Bank Sta=4991.6,4996.3
Exp/Cntr=0.3,0.1

Type RM Length L Ch R = 1,3893,264,264,264
BEGIN DESCRIPTION:
Mapping XS e68bd9b0
END DESCRIPTION:
XS GIS Cut Line= 3
      1694676.82      7059611.30      1694751.70      7059184.83
      1694768.98      7058841.36
#Sta/Elev= 30
  4563.9 1381.66  4577.3 1380.75  4582.4 1375.20  4618.0 1370.46  4636.7 1362.80
  4641.8 1358.38  4658.6 1352.28  4668.8 1350.01  4689.1 1350.85  4701.1 1345.92
  4750.0 1338.75  4770.3 1332.11  4869.1 1325.20  4874.2 1323.46  4928.5 1322.29
  5011.3 1312.30  5011.7 1311.80  5016.1 1312.30  5023.8 1312.31  5053.8 1325.01
  5063.9 1325.85  5103.9 1327.22  5123.9 1333.36  5160.5 1350.11  5173.9 1352.81
  5204.0 1353.90  5244.0 1373.35  5274.1 1385.43  5304.1 1401.14  5340.8 1409.85
#Mann=4,-1,0
  4563.9    0.07       0  5011.3    0.07       0  5016.1    0.07       0
  5063.9    0.16       0
Bank Sta=5011.3,5016.1
Exp/Cntr=0.3,0.1

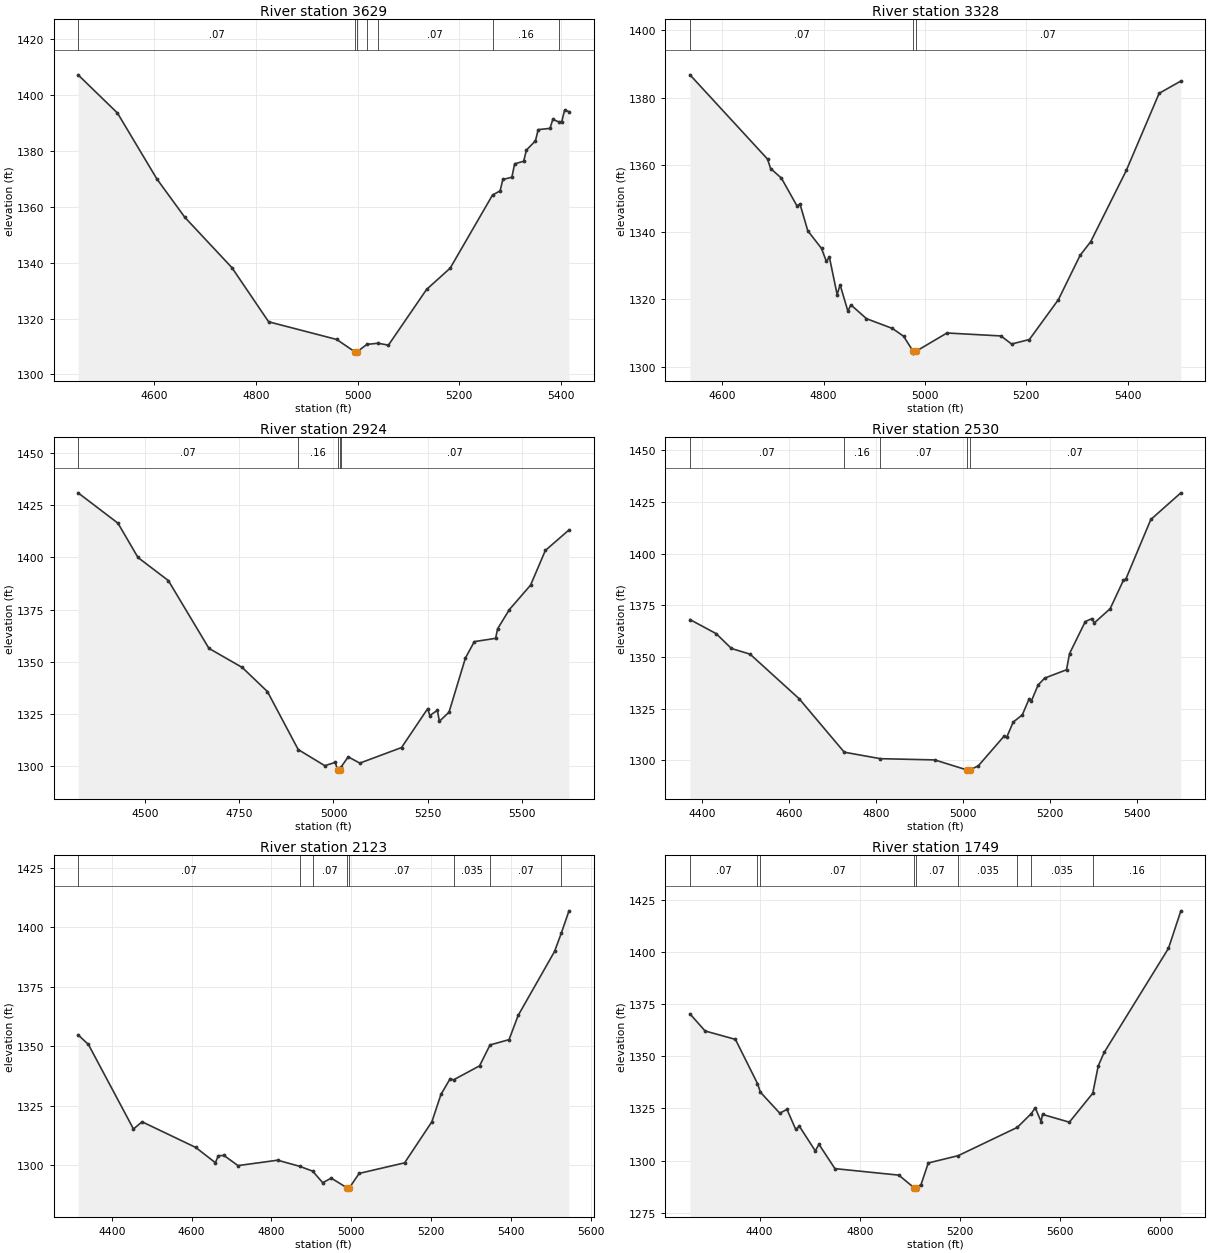
Type RM Length L Ch R = 1,3629,301,301,301
BEGIN DESCRIPTION:
Mapping XS 75e637fb
END DESCRIPTION:
XS GIS Cut Line= 3
      1695147.75      7059721.93      1695015.37      7059189.17
      1694845.01      7058808.30
#Sta/Elev= 30
  4449.8 1407.22  4527.3 1393.55  4604.8 1369.97  4659.9 1356.22  4752.7 1338.18
  4824.8 1318.83  4958.8 1312.50  4994.3 1308.11  4994.7 1307.61  4999.2 1308.11
  5018.1 1310.73  5040.0 1311.15  5060.6 1310.47  5135.7 1330.41  5182.1 1338.01
  5265.5 1364.20  5280.4 1365.68  5285.8 1369.76  5303.6 1370.57  5309.0 1375.36
  5326.8 1376.29  5332.2 1380.29  5350.0 1383.61  5355.4 1387.61  5378.6 1388.05
  5384.1 1391.24  5395.5 1390.42  5401.8 1390.45  5407.3 1394.56  5416.0 1394.06
#Mann=7,-1,0
  4449.8    0.07       0  4994.3    0.07       0  4999.2    0.07       0
  5018.1    0.16       0  5040.0    0.07       0  5265.5    0.16       0
  5395.5    0.07       0
Bank Sta=4994.3,4999.2
Exp/Cntr=0.3,0.1

Type RM Length L Ch R = 1,3328,404,404,404
BEGIN DESCRIPTION:
Mapping XS 21fd2a6a
END DESCRIPTION:
XS GIS Cut Line= 3
      1695513.56      7059468.39      1695270.51      7059073.43
      1694882.04      7058750.07
#Sta/Elev= 30
  4536.0 1386.76  4689.1 1361.71  4695.2 1358.90  4716.5 1356.05  4747.3 1347.78
  4753.2 1348.35  4768.6 1340.39  4795.7 1335.14  4805.3 1331.27  4811.2 1332.58
  4826.6 1321.40  4832.4 1324.32  4847.8 1316.49  4853.7 1318.36  4884.5 1314.25
  4935.7 1311.34  4957.9 1309.01  4976.7 1304.50  4977.1 1304.00  4981.7 1304.50
  5043.4 1309.99  5150.0 1309.11  5171.0 1306.71  5206.1 1308.05  5263.4 1319.91
  5306.2 1333.07  5327.2 1337.15  5397.5 1358.34  5462.3 1381.27  5505.2 1384.91
#Mann=3,-1,0
  4536.0    0.07       0  4976.7    0.07       0  4981.7    0.07       0
Bank Sta=4976.7,4981.7
Exp/Cntr=0.3,0.1

Type RM Length L Ch R = 1,2924,394,394,394
BEGIN DESCRIPTION:
Mapping XS 7571a0be
END DESCRIPTION:
XS GIS Cut Line= 3
      1695942.85      7059035.21      1695350.87      7058694.96
      1694765.77      7058488.35
#Sta/Elev= 30
  4322.0 1431.05  4427.9 1416.47  4481.0 1400.00  4561.6 1388.92  4669.4 1356.36
  4757.8 1347.18  4824.7 1335.61  4906.4 1307.77  4977.0 1300.02  5004.8 1301.62
  5010.9 1297.91  5011.3 1297.41  5016.1 1297.91  5019.8 1299.26  5039.1 1304.27
  5070.0 1301.26  5180.7 1308.73  5250.3 1327.45  5255.6 1324.09  5275.9 1326.60
  5281.2 1321.34  5306.8 1325.72  5350.4 1351.76  5374.0 1359.60  5430.5 1361.18
  5435.8 1365.76  5467.0 1374.98  5523.3 1386.73  5562.5 1403.37  5625.3 1413.23
#Mann=5,-1,0
  4322.0    0.07       0  4906.4    0.16       0  5010.9    0.07       0
  5016.1    0.16       0  5019.8    0.07       0
Bank Sta=5010.9,5016.1
Exp/Cntr=0.3,0.1

Type RM Length L Ch R = 1,2530,407,407,407
BEGIN DESCRIPTION:
Mapping XS 5bea528a
END DESCRIPTION:
XS GIS Cut Line= 3
      1695834.97      7058742.97      1695354.30      7058337.17
      1694934.35      7058063.71
#Sta/Elev= 30
  4371.5 1368.12  4431.9 1361.30  4467.0 1354.13  4509.9 1351.39  4623.1 1329.79
  4726.7 1303.99  4809.9 1300.85  4935.1 1300.25  5010.3 1295.33  5010.7 1294.83
  5015.5 1295.33  5035.5 1297.43  5094.5 1311.71  5100.5 1311.11  5115.6 1318.52
  5136.7 1322.06  5151.9 1329.57  5157.8 1328.87  5173.0 1336.46  5188.1 1339.81
  5238.4 1343.84  5245.4 1351.67  5281.6 1367.14  5296.8 1368.59  5302.7 1366.55
  5338.9 1373.37  5369.2 1387.02  5375.2 1387.78  5432.5 1416.51  5501.7 1429.40
#Mann=5,-1,0
  4371.5    0.07       0  4726.7    0.16       0  4809.9    0.07       0
  5010.3    0.07       0  5015.5    0.07       0
Bank Sta=5010.3,5015.5
Exp/Cntr=0.3,0.1

Type RM Length L Ch R = 1,2123,374,374,374
BEGIN DESCRIPTION:
Mapping XS cc4d0fce
END DESCRIPTION:
XS GIS Cut Line= 3
      1696096.49      7058512.96      1695589.76      7058047.46
      1695099.08      7057816.74
#Sta/Elev= 30
  4315.5 1354.77  4341.4 1350.72  4454.3 1315.23  4475.9 1318.25  4610.3 1307.49
  4659.6 1301.08  4667.0 1304.02  4681.2 1304.11  4716.3 1299.86  4815.6 1302.13
  4871.0 1299.55  4903.5 1297.52  4928.6 1292.67  4950.0 1294.60  4989.9 1290.48
  4990.3 1289.98  4995.2 1290.48  5019.9 1296.58  5133.8 1301.02  5202.2 1318.27
  5225.0 1329.77  5247.8 1336.30  5256.4 1335.86  5321.7 1341.75  5347.9 1350.53
  5395.6 1352.75  5418.4 1362.91  5509.6 1389.77  5526.5 1397.46  5545.8 1406.84
#Mann=8,-1,0
  4315.5    0.07       0  4871.0    0.16       0  4903.5    0.07       0
  4989.9    0.07       0  4995.2    0.07       0  5256.4   0.035       0
  5347.9    0.07       0  5526.5   0.035       0
Bank Sta=4989.9,4995.2
Exp/Cntr=0.3,0.1

Type RM Length L Ch R = 1,1749,613,613,613
BEGIN DESCRIPTION:
Mapping XS 9c6ce7a7
END DESCRIPTION:
XS GIS Cut Line= 3
      1696417.58      7058310.62      1695737.03      7057751.60
      1695309.99      7056758.65
#Sta/Elev= 30
  4121.8 1370.31  4182.2 1362.12  4303.5 1358.08  4391.6 1336.90  4403.2 1332.77
  4480.7 1322.69  4509.4 1324.51  4544.6 1314.88  4558.9 1316.46  4622.8 1304.58
  4637.1 1307.80  4701.0 1296.11  4956.4 1292.99  5018.7 1286.78  5019.1 1286.28
  5024.4 1286.78  5045.1 1288.46  5074.1 1298.82  5193.6 1302.33  5430.1 1315.91
  5485.7 1322.52  5501.5 1325.26  5525.0 1318.64  5530.5 1322.11  5637.8 1318.38
  5731.4 1332.27  5753.2 1345.38  5776.8 1351.80  6033.9 1401.74  6083.4 1419.72
#Mann=9,-1,0
  4121.8    0.07       0  4391.6   0.035       0  4403.2    0.07       0
  5018.7    0.07       0  5024.4    0.07       0  5193.6   0.035       0
  5430.1    0.07       0  5485.7   0.035       0  5731.4    0.16       0
Bank Sta=5018.7,5024.4
Exp/Cntr=0.3,0.1

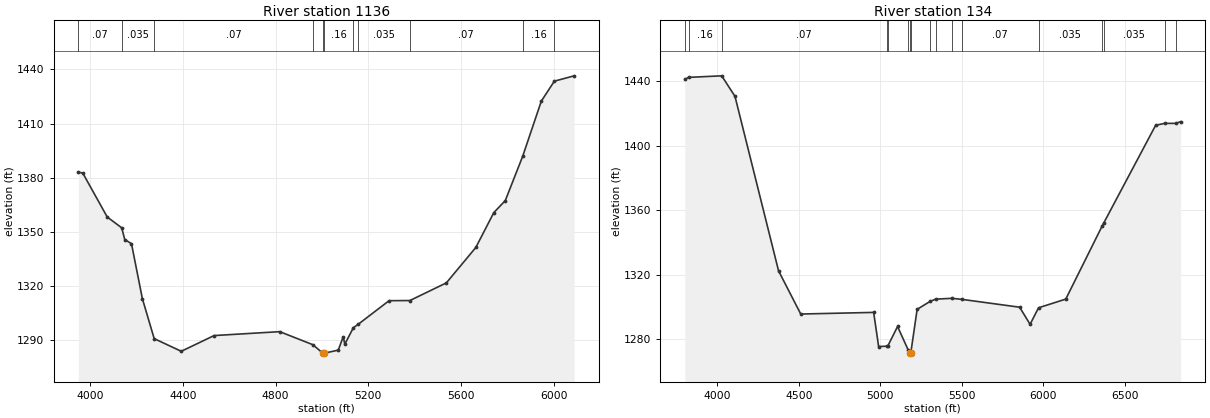
Type RM Length L Ch R = 1,1136,1002,1002,1002
BEGIN DESCRIPTION:
Mapping XS cd31568e
END DESCRIPTION:
XS GIS Cut Line= 3
      1696570.37      7058355.79      1696150.22      7057387.02
      1695382.84      7056619.63
#Sta/Elev= 30
  3947.8 1383.14  3967.2 1382.51  4072.6 1358.26  4135.1 1352.26  4148.4 1345.75
  4177.3 1343.50  4224.3 1313.08  4275.4 1290.94  4392.3 1283.93  4534.0 1292.63
  4817.4 1294.80  4960.6 1287.58  5003.9 1282.86  5004.4 1282.36  5009.6 1282.86
  5070.4 1284.59  5091.6 1291.96  5098.7 1287.88  5135.4 1296.96  5156.3 1298.86
  5289.6 1311.93  5379.6 1312.02  5537.1 1321.79  5664.4 1341.40  5742.1 1360.70
  5791.6 1367.34  5866.7 1391.85  5947.2 1422.38  6003.4 1433.43  6089.0 1436.39
#Mann=11,-1,0
  3947.8    0.07       0  4135.1   0.035       0  4275.4    0.07       0
  4960.6    0.16       0  5003.9    0.07       0  5009.6    0.16       0
  5135.4    0.07       0  5156.3   0.035       0  5379.6    0.07       0
  5866.7    0.16       0  6003.4    0.07       0
Bank Sta=5003.9,5009.6
Exp/Cntr=0.3,0.1

Type RM Length L Ch R = 1,134,0,0,0
BEGIN DESCRIPTION:
Mapping XS c6aa0eae
END DESCRIPTION:
XS GIS Cut Line= 3
      1696976.60      7058817.53      1696754.78      7057637.50
      1695418.80      7056367.34
#Sta/Elev= 30
  3799.3 1441.26  3822.1 1442.56  4025.9 1443.52  4107.4 1430.78  4375.0 1322.40
  4511.1 1295.60  4958.8 1296.61  4989.3 1275.42  5040.0 1275.62  5046.9 1276.00
  5105.6 1287.86  5172.0 1273.00  5180.3 1271.20  5180.8 1270.70  5186.4 1271.20
  5225.8 1298.52  5305.2 1303.43  5339.1 1304.84  5438.4 1305.35  5498.5 1304.74
  5855.2 1299.83  5919.1 1289.20  5971.2 1299.48  6138.3 1304.88  6361.7 1350.27
  6370.7 1352.00  6690.0 1412.79  6745.5 1414.00  6813.2 1413.98  6843.4 1415.03
#Mann=17,-1,0
  3799.3    0.07       0  3822.1    0.16       0  4025.9    0.07       0
  5040.0    0.16       0  5046.9    0.07       0  5172.0    0.16       0
  5180.3    0.07       0  5186.4    0.16       0  5305.2    0.07       0
  5339.1   0.035       0  5438.4    0.16       0  5498.5    0.07       0
  5971.2   0.035       0  6361.7    0.07       0  6370.7   0.035       0
  6745.5    0.07       0  6813.2   0.035       0
Bank Sta=5180.3,5186.4
Exp/Cntr=0.3,0.1

Chan Stop Cuts=-1