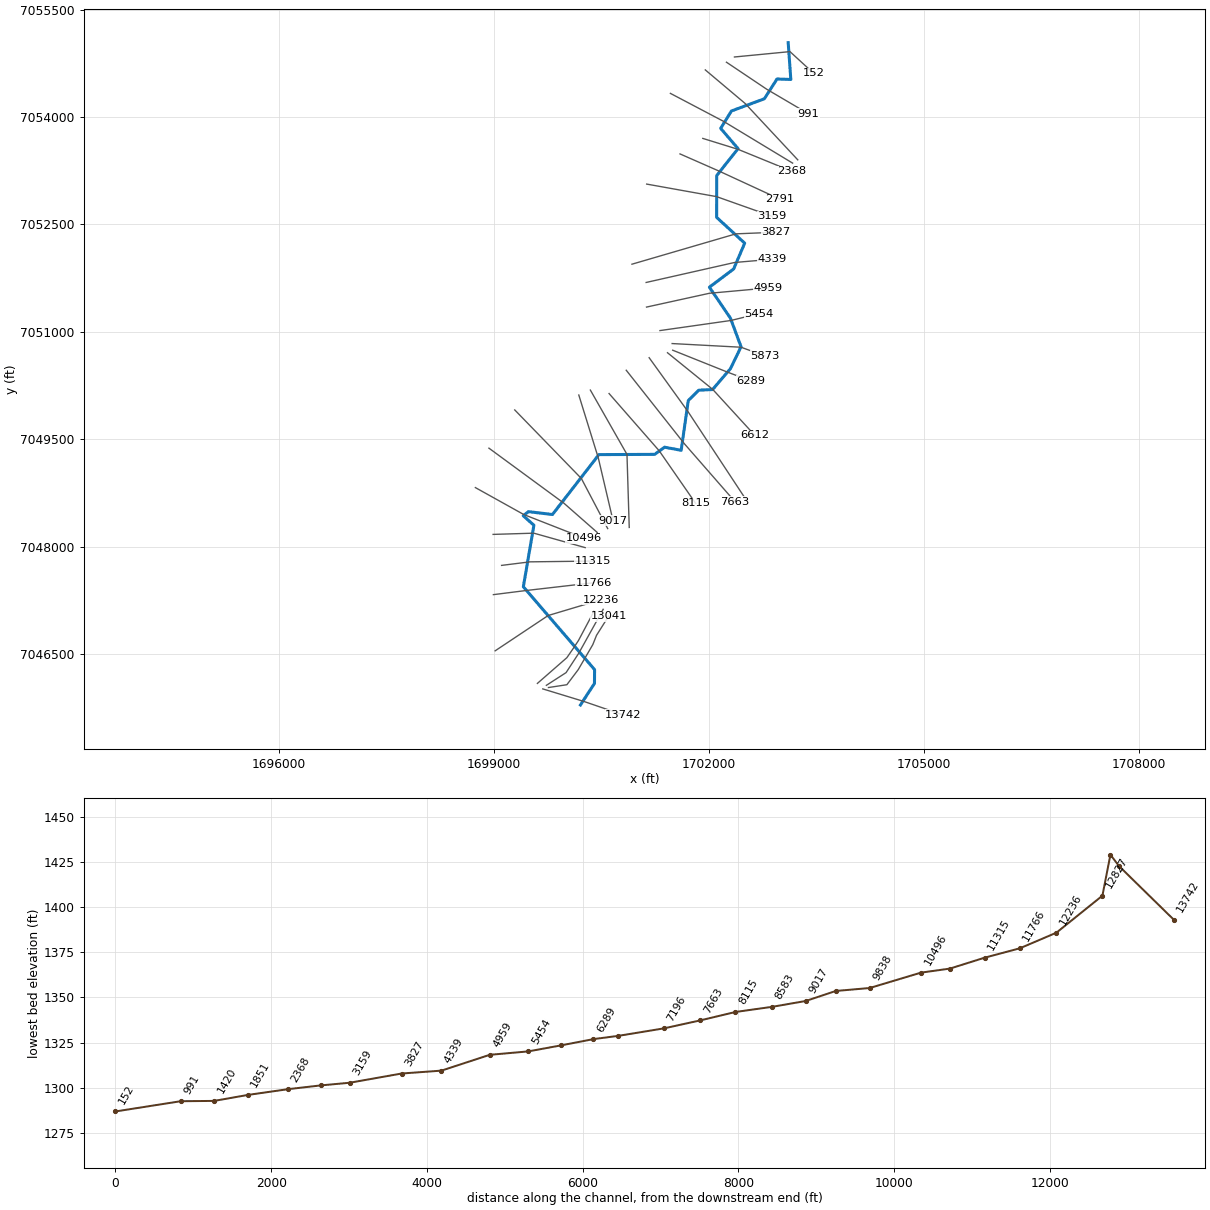
--- Chimney Creek 1198.prj (project) ---

Proj Title=Chimney Creek 1198 Base Level Engineering
Current Plan=p01
Default Exp/Contr=0.3,0.1
English Units
Geom File=g01
Flow File=f01
Plan File=p01
Y Axis Title=Elevation
X Axis Title(PF)=Main Channel Distance
X Axis Title(XS)=Station
BEGIN DESCRIPTION:
Chimney Creek 1198
END DESCRIPTION:
DSS Export Rating Curves= 0
DSS Export Rating Curve Sorted= 0
DSS Export Volume Flow Curves= 0
DXF OffsetX= 0
DXF OffsetY= 0
DXF ScaleX= 1
DXF ScaleY= 10

--- Chimney Creek 1198.p01 (plan) ---

Plan Title=Multiple Run
Short Identifier=Multiple
Geom File=g01
Flow File=f01
Subcritical Flow
K Sum by GR= 0
Std Step Tol= 0.01
Critical Tol= 0.01
Num of Std Step Trials= 20
Max Error Tol= 0.3
Flow Tol Ratio= 0.001
Split Flow NTrial= 30
Split Flow Tol= 0.02
Split Flow Ratio= 0.02
Log Output Level= 0
Friction Slope Method= 1
Unsteady Friction Slope Method= 2
Unsteady Bridges Friction Slope Method= 1
Parabolic Critical Depth
Global Vel Dist=  1 , 1 , 1
Global Log Level= 0
CheckData=True
Encroach Param= -1, 0, 0, 0
BEGIN DESCRIPTION:
Multiple Run
END DESCRIPTION:

--- Chimney Creek 1198.f01 (steady flow) ---

Flow Title=Multiple
Number of Profiles=7
Profile Names=10-year,25-year,50-year,1pct_min,100-year,1pct_plu,500-year
River Rch & RM= Chimney Creek 11,Reach-1,13742
     523     760     967     612    1222    2437    1975
River Rch & RM= Chimney Creek 11,Reach-1,7663
     841    1240    1590    1011    2018    4026    3281
River Rch & RM= Chimney Creek 11,Reach-1,2368
     906    1338    1717    1093    2181    4352    3554
Boundary for River Rch & Prof#=Chimney Creek 11,Reach-1,1
Up Type=0
Dn Type=3
Dn Slope=0.005
Boundary for River Rch & Prof#=Chimney Creek 11,Reach-1,2
Up Type=0
Dn Type=3
Dn Slope=0.005
Boundary for River Rch & Prof#=Chimney Creek 11,Reach-1,3
Up Type=0
Dn Type=3
Dn Slope=0.005
Boundary for River Rch & Prof#=Chimney Creek 11,Reach-1,4
Up Type=0
Dn Type=3
Dn Slope=0.005
Boundary for River Rch & Prof#=Chimney Creek 11,Reach-1,5
Up Type=0
Dn Type=3
Dn Slope=0.005
Boundary for River Rch & Prof#=Chimney Creek 11,Reach-1,6
Up Type=0
Dn Type=3
Dn Slope=0.005
Boundary for River Rch & Prof#=Chimney Creek 11,Reach-1,7
Up Type=0
Dn Type=3
Dn Slope=0.005

--- Chimney Creek 1198.g01 (geometry) ---

Geom Title=Existing Conditions
Program Version=4.10

River Reach=Chimney Creek 11,Reach-1
Reach XY= 30
        1700205.        7045788.      1700401.25      7046089.55
      1700402.83      7046282.56      1699408.46       7047439.5
      1699555.75      7048298.67      1699406.48      7048432.12
      1699479.78      7048488.36       1699814.8      7048448.47
      1700463.28      7049284.94      1701241.14      7049288.54
      1701379.89      7049388.32      1701611.39      7049345.34
      1701710.46      7050040.45      1701856.65      7050184.84
      1702049.38      7050193.56      1702299.48      7050485.57
      1702447.12      7050791.22      1702299.17       7051190.3
      1702005.18      7051622.91      1702344.49      7051878.19
      1702497.72      7052238.06      1702106.19      7052598.48
      1702107.24      7053182.07      1702405.48      7053558.16
      1702162.82      7053841.04      1702313.62      7054084.16
      1702772.21      7054254.27      1702948.94      7054530.52
      1703141.62      7054524.12        1703105.        7055038.

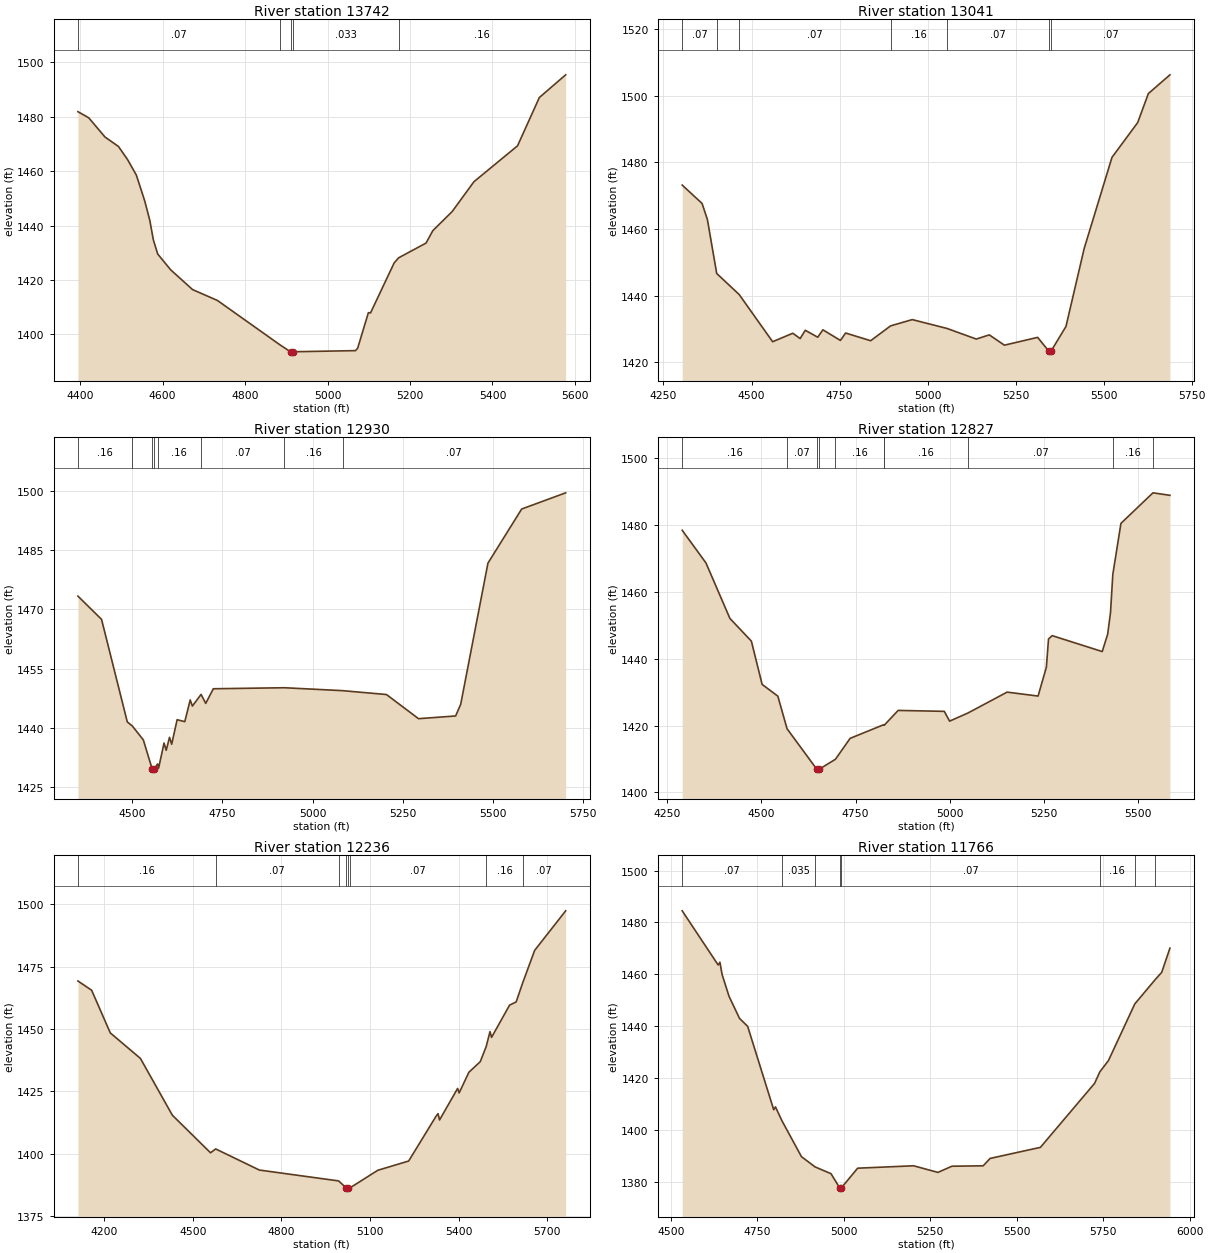
Type RM Length L Ch R = 1 ,13742   ,701,701,701
BEGIN DESCRIPTION:
Chimney Creek 1198 29.0
END DESCRIPTION:
XS GIS Cut Line= 3
      1699679.96      7046013.01      1700259.04      7045836.09
      1700805.36      7045648.61
#Sta/Elev= 30
  4394.5 1481.91  4420.7 1479.66  4460.1  1472.6  4492.9  1469.1  4514.8 1464.32
  4536.2  1458.6  4556.6 1449.07    4569 1441.85  4577.5 1434.75    4588 1429.57
  4619.4 1423.76  4672.6 1416.48    4733 1412.47  4884.7 1396.15  4910.2 1393.61
  4910.5 1393.11  4915.1 1393.61  5067.8 1394.03  5073.1 1394.93  5099.1 1407.99
  5104.3  1407.9  5161.6 1426.29  5172.4 1428.16  5238.9 1433.58  5255.4 1438.15
  5302.3 1445.17  5355.2 1456.16  5460.9 1469.35  5513.8 1487.11  5577.6 1495.46
#Mann= 5 ,-1 , 0
  4394.5     .07       0  4884.7    .033       0  4910.2    .033       0
  4915.1    .033       0  5172.4     .16       0
Bank Sta=4910.2,4915.1
XS Rating Curve= 0 ,0
Exp/Cntr=0.3,0.1

Type RM Length L Ch R = 1 ,13041   ,111,111,111
BEGIN DESCRIPTION:
Mapping XS 3f94c53f
END DESCRIPTION:
XS GIS Cut Line= 6
      1699759.12      7046032.18      1700015.99      7046071.51
      1700174.85      7046282.45      1700377.97      7046631.41
      1700430.05      7046761.62      1700599.31      7047029.82
#Sta/Elev= 30
  4303.2  1473.2  4359.7 1467.68  4374.8 1462.83  4401.2 1446.63  4465.1 1440.29
    4560 1426.11  4617.3 1428.66  4638.1 1427.06  4652.7 1429.55  4688.1 1427.46
  4702.7 1429.69  4752.6  1426.5  4767.2 1428.73  4838.4 1426.41  4895.1 1430.88
  4956.6 1432.76  5054.9 1430.11  5138.3 1426.91  5175.3 1428.17  5218.2 1425.07
  5312.6 1427.42  5345.1 1423.18  5345.5 1422.68  5350.1 1423.18  5393.1 1430.71
  5444.9 1454.19  5523.7 1481.54  5596.7 1491.99    5627 1500.72  5688.3 1506.36
#Mann= 7 ,-1 , 0
  4303.2     .07       0  4401.2     .16       0  4465.1     .07       0
  4895.1     .16       0  5054.9     .07       0  5345.1     .07       0
  5350.1     .07       0
Bank Sta=5345.1,5350.1
XS Rating Curve= 0 ,0
Exp/Cntr=0.3,0.1

Type RM Length L Ch R = 1 ,12930   ,103,103,103
BEGIN DESCRIPTION:
Chimney Creek 1198 28.0
END DESCRIPTION:
XS GIS Cut Line= 4
      1699730.01      7046063.01      1700005.05      7046240.61
      1700181.86      7046511.16      1700522.93      7047124.62
#Sta/Elev= 30
  4349.4 1473.38  4414.9 1467.49  4486.3  1441.5  4500.3 1440.46  4530.8 1436.94
  4555.4 1429.53  4555.8 1429.03  4560.4 1429.53  4570.4 1430.84  4573.1 1429.77
  4588.2 1436.15  4594.2 1434.31  4603.4  1437.6  4609.4 1435.84  4624.5 1442.06
  4645.7 1441.57  4660.8 1447.07  4666.8 1445.52  4690.9 1448.47  4703.8  1446.2
  4724.9  1449.9  4922.1 1450.16  5083.4 1449.42    5205 1448.44  5293.9 1442.32
  5396.8 1443.01  5410.9 1445.97  5486.4 1481.73  5579.9 1495.44  5701.9 1499.55
#Mann= 8 ,-1 , 0
  4349.4     .16       0  4500.3     .07       0  4555.4     .07       0
  4560.4     .07       0  4570.4     .16       0  4690.9     .07       0
  4922.1     .16       0  5083.4     .07       0
Bank Sta=4555.4,4560.4
XS Rating Curve= 0 ,0
Exp/Cntr=0.3,0.1

Type RM Length L Ch R = 1 ,12827   ,591,591,591
BEGIN DESCRIPTION:
Chimney Creek 1198 27.0
END DESCRIPTION:
XS GIS Cut Line= 5
      1699604.55      7046089.76      1700015.99      7046449.12
      1700109.11       7046583.9      1700177.45        7046688.
      1700393.07      7047093.96
#Sta/Elev= 30
  4289.9 1478.46  4352.9  1468.7  4416.5 1452.07  4473.5 1445.26    4502 1432.31
  4543.7 1428.79  4568.1 1419.04  4647.5 1406.84  4647.9 1406.34  4652.5 1406.84
  4696.6  1409.9  4735.5 1416.15    4825 1420.26    4826 1420.08    4863 1424.52
  4985.4 1424.24  4999.5 1421.31  5048.5 1423.76  5152.1    1430  5234.3 1428.82
  5256.3 1437.47    5262 1445.91  5271.7 1446.91  5404.5 1442.15  5418.9 1447.31
  5426.5  1453.8  5432.6 1465.23  5454.2 1480.54  5539.2 1489.68  5584.2 1488.93
#Mann= 10 ,-1 , 0
  4289.9     .16       0  4568.1     .07       0  4647.5     .07       0
  4652.5     .07       0  4696.6     .16       0    4825     .07       0
    4826     .16       0  5048.5     .07       0  5432.6     .16       0
  5539.2     .07       0
Bank Sta=4647.5,4652.5
XS Rating Curve= 0 ,0
Exp/Cntr=0.3,0.1

Type RM Length L Ch R = 1 ,12236   ,470,470,470
BEGIN DESCRIPTION:
Chimney Creek 1198 26.0
END DESCRIPTION:
XS GIS Cut Line= 3
      1699014.98       7046544.8        1699755.        7047038.
      1700485.57      7047256.29
#Sta/Elev= 30
  4110.7 1469.26  4157.2 1465.54  4220.3 1448.46  4322.4 1438.22  4430.6 1415.46
  4559.8 1400.41  4577.2 1401.96  4725.1  1393.5  4993.7 1389.14  5019.2 1386.35
  5019.6 1385.85  5024.3 1386.35  5032.3 1386.37  5126.4 1393.41  5230.9 1397.12
  5323.6 1415.06  5330.3 1416.09  5335.5 1413.57  5396.6  1426.2  5401.8  1424.4
  5434.9  1432.7  5473.2 1436.91  5493.5 1443.01  5506.3 1448.98  5511.6 1446.67
  5572.6 1459.58  5594.9 1460.87    5617 1468.51  5657.5 1481.52  5762.5 1497.37
#Mann= 8 ,-1 , 0
  4110.7     .16       0  4577.2     .07       0  4993.7    .035       0
  5019.2    .035       0  5024.3    .035       0  5032.3     .07       0
  5493.5     .16       0    5617     .07       0
Bank Sta=5019.2,5024.3
XS Rating Curve= 0 ,0
Exp/Cntr=0.3,0.1

Type RM Length L Ch R = 1 ,11766   ,451,451,451
BEGIN DESCRIPTION:
Chimney Creek 1198 25.0
END DESCRIPTION:
XS GIS Cut Line= 3
      1698990.65       7047329.5        1699455.        7047388.
      1700391.67      7047495.96
#Sta/Elev= 30
  4532.3 1484.49  4636.4  1463.6  4641.4 1464.69  4647.6    1460  4667.7 1451.56
    4698 1443.05  4721.7 1439.95    4797 1407.82  4802.1  1408.9  4820.4 1403.68
  4877.3 1389.72  4916.7 1385.77  4962.7 1383.17  4987.7 1377.71  4988.1 1377.21
  4992.8 1377.71  5039.8 1385.28  5201.6 1386.21  5272.1 1383.66  5312.4 1386.04
    5403  1386.2  5423.1 1389.05  5568.5 1393.31  5725.1 1417.96  5740.4 1422.41
  5765.4 1426.78  5841.5 1448.59  5900.5 1457.97  5919.4 1460.77  5943.2 1470.11
#Mann= 8 ,-1 , 0
  4532.3     .07       0  4820.4    .035       0  4916.7     .07       0
  4987.7     .07       0  4992.8     .07       0  5740.4     .16       0
  5841.5     .07       0  5900.5     .16       0
Bank Sta=4987.7,4992.8
XS Rating Curve= 0 ,0
Exp/Cntr=0.3,0.1

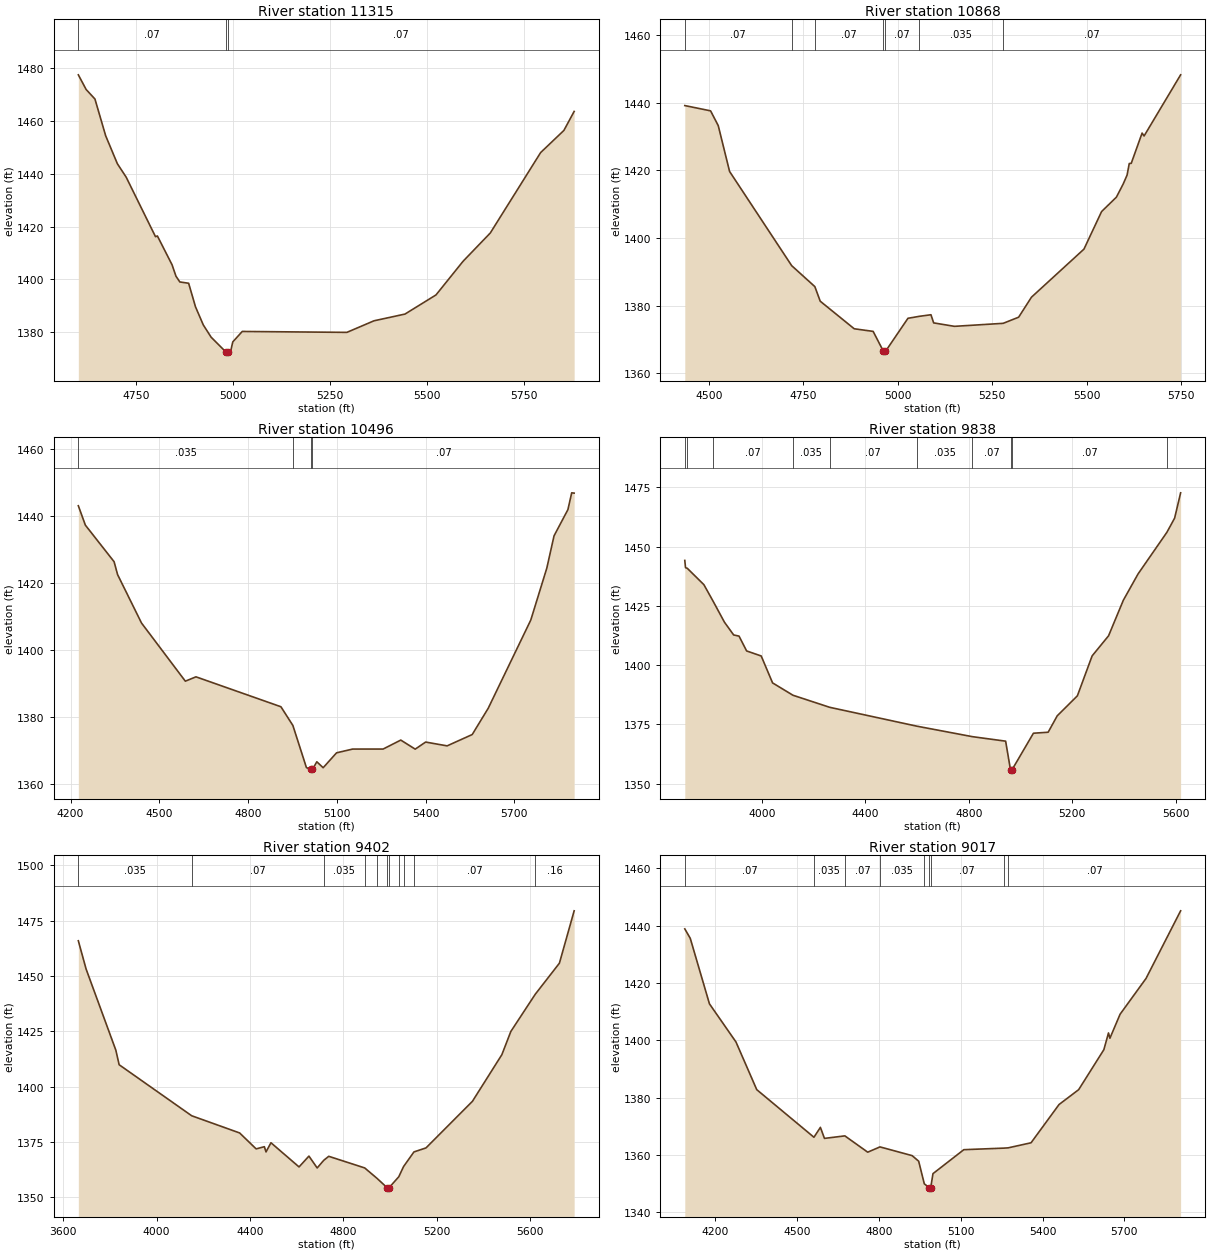
Type RM Length L Ch R = 1 ,11315   ,447,447,447
BEGIN DESCRIPTION:
Chimney Creek 1198 24.0
END DESCRIPTION:
XS GIS Cut Line= 3
      1699104.98        7047738.        1699501.       7047787.5
      1700381.53      7047798.23
#Sta/Elev= 30
  4600.9 1477.57  4621.1    1472  4643.8 1468.39  4671.5 1454.45  4701.7 1443.85
  4724.4 1438.76    4800 1416.21    4805 1416.45  4842.8 1405.54  4852.9  1401.2
  4862.9 1399.02  4885.6 1398.53  4903.3  1389.6  4923.4 1382.73  4943.6 1378.08
  4981.3 1372.53  4981.7 1372.03  4986.5 1372.53    4994 1372.69  4999.5 1376.28
    5024 1380.25    5294  1379.9    5364 1384.29    5444 1386.84    5524  1394.1
    5594 1406.88  5664.1 1417.58  5794.1 1448.09  5854.1 1456.48  5880.6 1463.69
#Mann= 3 ,-1 , 0
  4600.9     .07       0  4981.3     .07       0  4986.5     .07       0
Bank Sta=4981.3,4986.5
XS Rating Curve= 0 ,0
Exp/Cntr=0.3,0.1

Type RM Length L Ch R = 1 ,10868   ,372,372,372
BEGIN DESCRIPTION:
Chimney Creek 1198 23.0
END DESCRIPTION:
XS GIS Cut Line= 3
      1698986.46      7048170.79        1699555.        7048188.
      1700271.45       7047986.3
#Sta/Elev= 30
  4435.8 1439.18  4504.1 1437.62  4524.4 1433.25  4554.4  1419.7  4718.9 1391.84
  4780.2 1385.65  4794.5 1381.33  4884.5 1373.18  4934.6 1372.41    4962 1366.48
  4962.4 1365.98  4967.2 1366.48  5026.8 1376.28  5056.3 1376.85  5087.7 1377.33
  5094.9 1374.92    5150  1373.9  5278.9 1374.79  5319.9  1376.6  5353.9 1382.52
  5492.9 1396.73  5539.6 1407.84  5578.9 1412.11  5596.8 1415.99  5607.1 1418.63
  5612.9 1422.05  5618.1 1422.09  5646.9 1431.05  5652.1 1430.18  5748.9 1448.27
#Mann= 7 ,-1 , 0
  4435.8     .07       0  4718.9    .035       0  4780.2     .07       0
    4962     .07       0  4967.2     .07       0  5056.3    .035       0
  5278.9     .07       0
Bank Sta=4962,4967.2
XS Rating Curve= 0 ,0
Exp/Cntr=0.3,0.1

Type RM Length L Ch R = 1 ,10496   ,658,658,658
BEGIN DESCRIPTION:
Chimney Creek 1198 22.0
END DESCRIPTION:
XS GIS Cut Line= 3
      1698739.04      7048824.44      1699415.01      7048448.04
      1700254.64      7048118.72
#Sta/Elev= 30
  4226.3 1443.16  4250.1 1437.36  4347.2 1426.41    4359 1422.55  4439.8 1408.07
  4587.9 1390.66  4623.9 1391.96  4910.9 1383.01  4951.3 1377.42  4997.1  1364.8
  5012.3 1364.24  5012.7 1363.74  5017.6 1364.24  5032.2 1366.54  5053.7 1364.76
    5099 1369.22  5153.2 1370.34  5256.4 1370.35    5316 1373.03  5364.8 1370.32
    5400 1372.44  5472.6  1371.3  5557.4 1374.69  5611.6 1382.57  5755.3 1408.95
  5809.5  1424.5  5833.9 1434.15  5880.8 1442.01  5893.6 1447.03  5901.9 1446.94
#Mann= 4 ,-1 , 0
  4226.3    .035       0  4951.3     .07       0  5012.3     .07       0
  5017.6     .07       0
Bank Sta=5012.3,5017.6
XS Rating Curve= 0 ,0
Exp/Cntr=0.3,0.1

Type RM Length L Ch R = 1 ,9838    ,436,436,436
BEGIN DESCRIPTION:
Chimney Creek 1198 21.0
END DESCRIPTION:
XS GIS Cut Line= 3
       1698928.3      7049375.06      1699974.09      7048607.05
      1700438.74      7048198.83
#Sta/Elev= 30
  3702.5 1444.19  3705.3 1441.13    3712 1440.88  3776.3 1433.95  3811.3 1427.09
  3855.8 1418.11  3891.3 1412.73  3912.1 1412.24  3941.4 1405.98  3997.8 1403.85
  4041.7 1392.49  4120.4 1387.28  4262.5 1382.18  4598.7 1374.23  4813.8 1369.79
  4942.3 1367.89  4961.2 1355.74  4961.6 1355.24  4966.6 1355.74  5049.7 1371.24
  5106.6 1371.66  5141.7 1378.59  5219.6 1387.04  5276.5 1403.88  5340.1 1412.38
    5397 1427.35  5453.8 1438.45  5565.5 1456.07  5595.3 1462.04  5618.5 1472.73
#Mann= 10 ,-1 , 0
  3702.5     .07       0    3712    .035       0  3811.3     .07       0
  4120.4    .035       0  4262.5     .07       0  4598.7    .035       0
  4813.8     .07       0  4961.2     .07       0  4966.6     .07       0
  5565.5     .16       0
Bank Sta=4961.2,4966.6
XS Rating Curve= 0 ,0
Exp/Cntr=0.3,0.1

Type RM Length L Ch R = 1 ,9402    ,385,385,385
BEGIN DESCRIPTION:
Chimney Creek 1198 20.0
END DESCRIPTION:
XS GIS Cut Line= 3
      1699288.55       7049908.9      1700218.63      7048951.21
      1700585.71      7048252.01
#Sta/Elev= 30
    3665 1465.92  3698.4 1453.11  3825.8 1416.42  3839.9 1409.86  4150.8 1386.78
  4356.2 1379.01  4426.9  1371.8  4462.2 1372.79  4469.3 1370.44  4490.5 1374.57
  4610.8 1363.64  4653.2 1368.54  4688.5 1363.17  4716.7 1366.64  4738.1 1368.44
  4892.1 1363.19  4944.9 1358.48  4989.8  1354.1  4990.3  1353.6  4995.3  1354.1
  5038.1 1359.18  5058.8 1363.83  5103.2 1370.43  5154.8 1372.24  5353.8 1393.32
  5479.9 1414.41  5518.4 1424.91    5623 1441.74  5726.5 1455.79  5789.7 1479.47
#Mann= 11 ,-1 , 0
    3665    .035       0  4150.8     .07       0  4716.7    .035       0
  4892.1     .07       0  4944.9    .035       0  4989.8    .035       0
  4995.3    .035       0  5038.1     .07       0  5058.8    .035       0
  5103.2     .07       0    5623     .16       0
Bank Sta=4989.8,4995.3
XS Rating Curve= 0 ,0
Exp/Cntr=0.3,0.1

Type RM Length L Ch R = 1 ,9017    ,434,434,434
BEGIN DESCRIPTION:
Chimney Creek 1198 19.0
END DESCRIPTION:
XS GIS Cut Line= 3
      1700182.62       7050117.3        1700455.        7049238.
      1700660.02      7048363.95
#Sta/Elev= 30
  4088.1 1438.91  4108.1 1435.62  4178.5 1412.75  4275.8 1399.43    4352 1382.78
  4561.7 1366.17  4585.4 1369.62  4600.3 1365.77  4675.1 1366.65  4758.9 1360.96
  4803.9  1362.8  4921.9 1359.75  4945.8  1357.8  4966.4 1349.93  4984.2 1348.56
  4984.7 1348.06  4989.9 1348.56  4998.2 1353.46  5111.3 1361.83  5257.5 1362.37
    5274 1362.47  5357.9 1364.24  5460.6  1377.6  5532.5 1382.78  5624.9 1396.74
  5641.9 1402.58  5647.1 1400.74  5684.4 1409.11  5779.5  1421.6  5906.4 1445.21
#Mann= 9 ,-1 , 0
  4088.1     .07       0  4561.7    .035       0  4675.1     .07       0
  4803.9    .035       0  4966.4     .07       0  4984.2     .07       0
  4989.9     .07       0  5257.5    .035       0    5274     .07       0
Bank Sta=4984.2,4989.9
XS Rating Curve= 0 ,0
Exp/Cntr=0.3,0.1

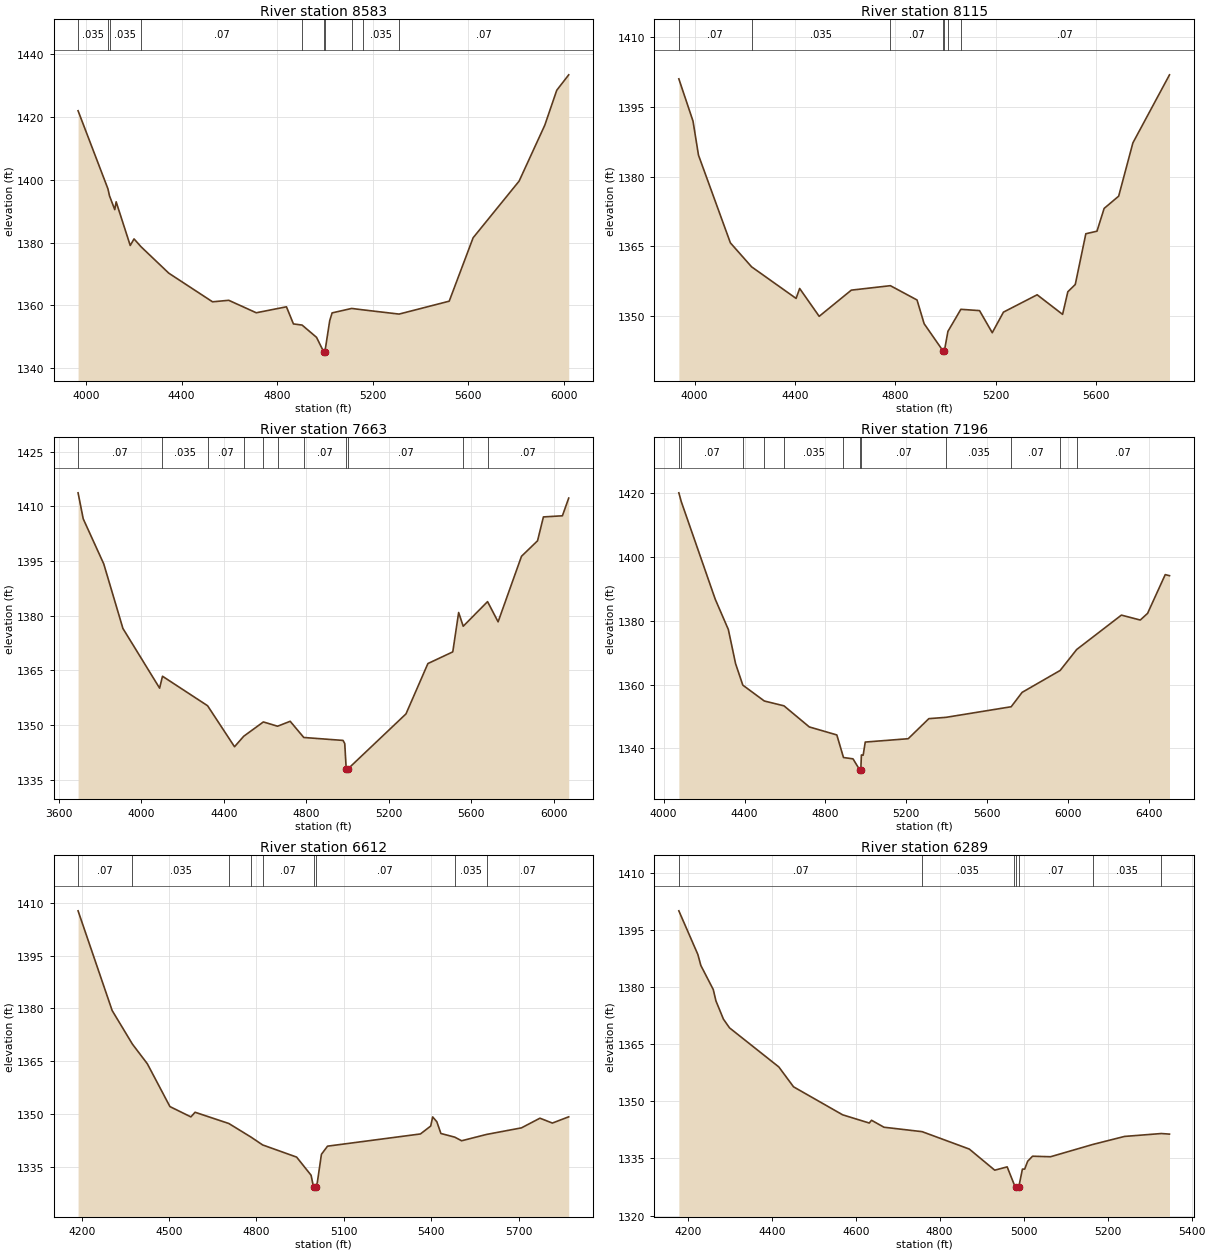
Type RM Length L Ch R = 1 ,8583    ,468,468,468
BEGIN DESCRIPTION:
Chimney Creek 1198 18.0
END DESCRIPTION:
XS GIS Cut Line= 3
      1700343.93      7050186.31        1700855.        7049288.
      1700886.48       7048267.9
#Sta/Elev= 30
  3966.5 1421.98  4091.4 1397.15  4098.2 1394.87  4120.1 1390.49  4125.9 1392.99
  4184.9 1379.09  4200.8 1381.18  4229.7 1378.71  4346.4 1370.26  4529.4 1361.15
  4597.3 1361.63  4712.5 1357.66  4838.9 1359.56  4868.1 1354.11  4904.4 1353.74
  4964.7 1349.85  4994.3 1345.31  4994.7 1344.81    5000 1345.31    5020 1355.14
    5030 1357.62    5112 1359.04  5157.8  1358.6  5310.4 1357.24  5520.3 1361.35
  5620.3 1381.53    5813 1399.59  5920.4 1417.38  5970.5 1428.51  6020.6 1433.42
#Mann= 10 ,-1 , 0
  3966.5    .035       0  4091.4     .07       0  4098.2    .035       0
  4229.7     .07       0  4904.4    .035       0  4994.3    .035       0
    5000    .035       0    5112     .07       0  5157.8    .035       0
  5310.4     .07       0
Bank Sta=4994.3,5000
XS Rating Curve= 0 ,0
Exp/Cntr=0.3,0.1

Type RM Length L Ch R = 1 ,8115    ,452,452,452
BEGIN DESCRIPTION:
Chimney Creek 1198 17.0
END DESCRIPTION:
XS GIS Cut Line= 3
      1700605.01      7050137.98        1701305.        7049338.
      1701813.56      7048603.83
#Sta/Elev= 30
    3937 1401.07  3993.5 1391.97  4015.3 1384.64  4142.5 1365.74  4226.9 1360.58
  4404.4 1353.77  4418.7 1355.91  4496.5 1349.91  4624.6 1355.55  4780.4 1356.51
  4886.6 1353.43    4915 1348.31    4990 1342.48  4990.5 1341.98  4995.7 1342.48
  5009.8 1346.67  5061.3 1351.42  5135.8 1351.14  5186.5 1346.38  5231.1 1350.81
  5365.5 1354.55  5466.9 1350.33  5487.8  1355.2  5517.5 1356.77  5559.6  1367.7
    5604 1368.25  5632.6 1373.16  5690.5  1375.8  5747.2 1387.28  5893.1 1401.94
#Mann= 7 ,-1 , 0
    3937     .07       0  4226.9    .035       0  4780.4     .07       0
    4990     .07       0  4995.7     .07       0  5009.8     .16       0
  5061.3     .07       0
Bank Sta=4990,4995.7
XS Rating Curve= 0 ,0
Exp/Cntr=0.3,0.1

Type RM Length L Ch R = 1 ,7663    ,467,467,467
BEGIN DESCRIPTION:
Chimney Creek 1198 16.0
END DESCRIPTION:
XS GIS Cut Line= 3
      1700844.82      7050463.18        1701655.        7049438.
      1702360.24      7048630.08
#Sta/Elev= 30
  3692.7 1413.67  3717.8 1406.52  3817.2 1394.18  3910.2 1376.46  4088.1 1360.09
    4102 1363.36  4320.7 1355.27  4451.3 1344.02    4496  1346.9  4591.2 1350.82
    4660 1349.65  4721.2    1351  4787.1 1346.56  4977.7 1345.75  4985.8 1344.88
    4993 1337.83  4993.5 1337.33  4999.3 1337.83  5282.7 1353.03    5389 1366.84
  5509.6 1370.04  5538.1 1380.84  5560.2 1377.07  5678.3 1383.83  5729.4 1378.28
  5842.8 1396.26  5920.6 1400.51  5949.1 1407.06  6041.2 1407.37  6071.8 1412.23
#Mann= 11 ,-1 , 0
  3692.7     .07       0    4102    .035       0  4320.7     .07       0
    4496    .035       0  4591.2     .07       0    4660    .035       0
  4787.1     .07       0    4993     .07       0  4999.3     .07       0
  5560.2    .035       0  5678.3     .07       0
Bank Sta=4993,4999.3
XS Rating Curve= 0 ,0
Exp/Cntr=0.3,0.1

Type RM Length L Ch R = 1 ,7196    ,584,584,584
BEGIN DESCRIPTION:
Chimney Creek 1198 15.0
END DESCRIPTION:
XS GIS Cut Line= 3
      1701164.41      7050638.33        1701705.        7049888.
       1702530.8      7048634.33
#Sta/Elev= 30
  4075.2 1420.05  4086.9 1417.36  4255.1 1386.75  4320.1 1377.23  4355.7 1366.57
  4391.6 1359.83  4497.8 1354.87  4595.1 1353.35  4720.2 1346.75  4856.4 1344.24
  4889.3 1337.17  4936.2 1336.76  4968.6 1333.41  4969.1 1332.91  4974.9 1333.41
  4977.9 1337.98  4986.5 1337.89  4996.9 1342.01  5209.3 1343.06  5311.3 1349.34
  5396.1 1349.75  5718.5 1353.07  5772.5 1357.57  5960.6 1364.43  6042.3 1370.99
  6263.4 1381.76  6356.7 1380.22  6392.8  1382.3  6480.2 1394.44  6501.2 1394.11
#Mann= 12 ,-1 , 0
  4075.2    .035       0  4086.9     .07       0  4391.6    .035       0
  4497.8     .07       0  4595.1    .035       0  4889.3     .07       0
  4968.6     .07       0  4974.9     .07       0  5396.1    .035       0
  5718.5     .07       0  5960.6    .035       0  6042.3     .07       0
Bank Sta=4968.6,4974.9
XS Rating Curve= 0 ,0
Exp/Cntr=0.3,0.1

Type RM Length L Ch R = 1 ,6612    ,323,323,323
BEGIN DESCRIPTION:
Chimney Creek 1198 14.0
END DESCRIPTION:
XS GIS Cut Line= 3
      1701420.48      7050707.76      1702051.29      7050196.16
      1702639.68      7049553.53
#Sta/Elev= 30
  4187.8 1407.68  4304.8 1379.41  4374.2  1369.9  4425.4 1364.33    4503 1352.18
  4574.9 1349.26  4589.3 1350.57    4705 1347.39  4781.2 1343.53  4821.1 1341.31
  4937.7 1337.86  4987.3 1332.72  4995.9 1329.28  4996.4 1328.78  5002.5 1329.28
  5008.6  1330.6  5022.8 1338.65  5043.7 1340.96  5362.5 1344.42  5397.7 1346.66
  5404.5 1349.25  5418.7  1347.9  5432.8 1344.55  5480.3 1343.52  5503.8 1342.49
  5589.6 1344.29  5709.1 1346.15  5772.6 1348.89  5815.2 1347.51  5871.3 1349.28
#Mann= 9 ,-1 , 0
  4187.8     .07       0  4374.2    .035       0    4705     .07       0
  4781.2    .035       0  4821.1     .07       0  4995.9     .07       0
  5002.5     .07       0  5480.3    .035       0  5589.6     .07       0
Bank Sta=4995.9,5002.5
XS Rating Curve= 0 ,0
Exp/Cntr=0.3,0.1

Type RM Length L Ch R = 1 ,6289    ,416,416,416
BEGIN DESCRIPTION:
Chimney Creek 1198 13.0
END DESCRIPTION:
XS GIS Cut Line= 3
      1701492.99       7050743.1        1702255.        7050438.
      1702580.04      7050315.16
#Sta/Elev= 30
  4178.9 1400.09  4224.2 1388.62  4231.3 1385.73  4260.9  1379.4  4267.2 1376.43
  4285.1 1371.62  4299.6 1369.33    4417 1359.06    4452 1353.84  4568.9 1346.48
  4632.3 1344.32  4637.7 1345.05  4667.3 1343.22  4758.3 1342.05  4870.5 1337.48
  4931.1 1331.93  4960.7  1332.8  4976.9  1328.3  4981.6 1327.45  4982.1 1326.95
  4988.2 1327.45    4997 1332.21  5002.4 1332.21  5009.5 1334.28  5021.1  1335.6
  5063.9 1335.46  5164.9  1338.7  5240.2  1340.8  5327.6 1341.56  5347.2 1341.41
#Mann= 7 ,-1 , 0
  4178.9     .07       0  4758.3    .035       0  4976.9     .07       0
  4981.6     .07       0  4988.2     .07       0  5164.9    .035       0
  5327.6     .07       0
Bank Sta=4981.6,4988.2
XS Rating Curve= 0 ,0
Exp/Cntr=0.3,0.1

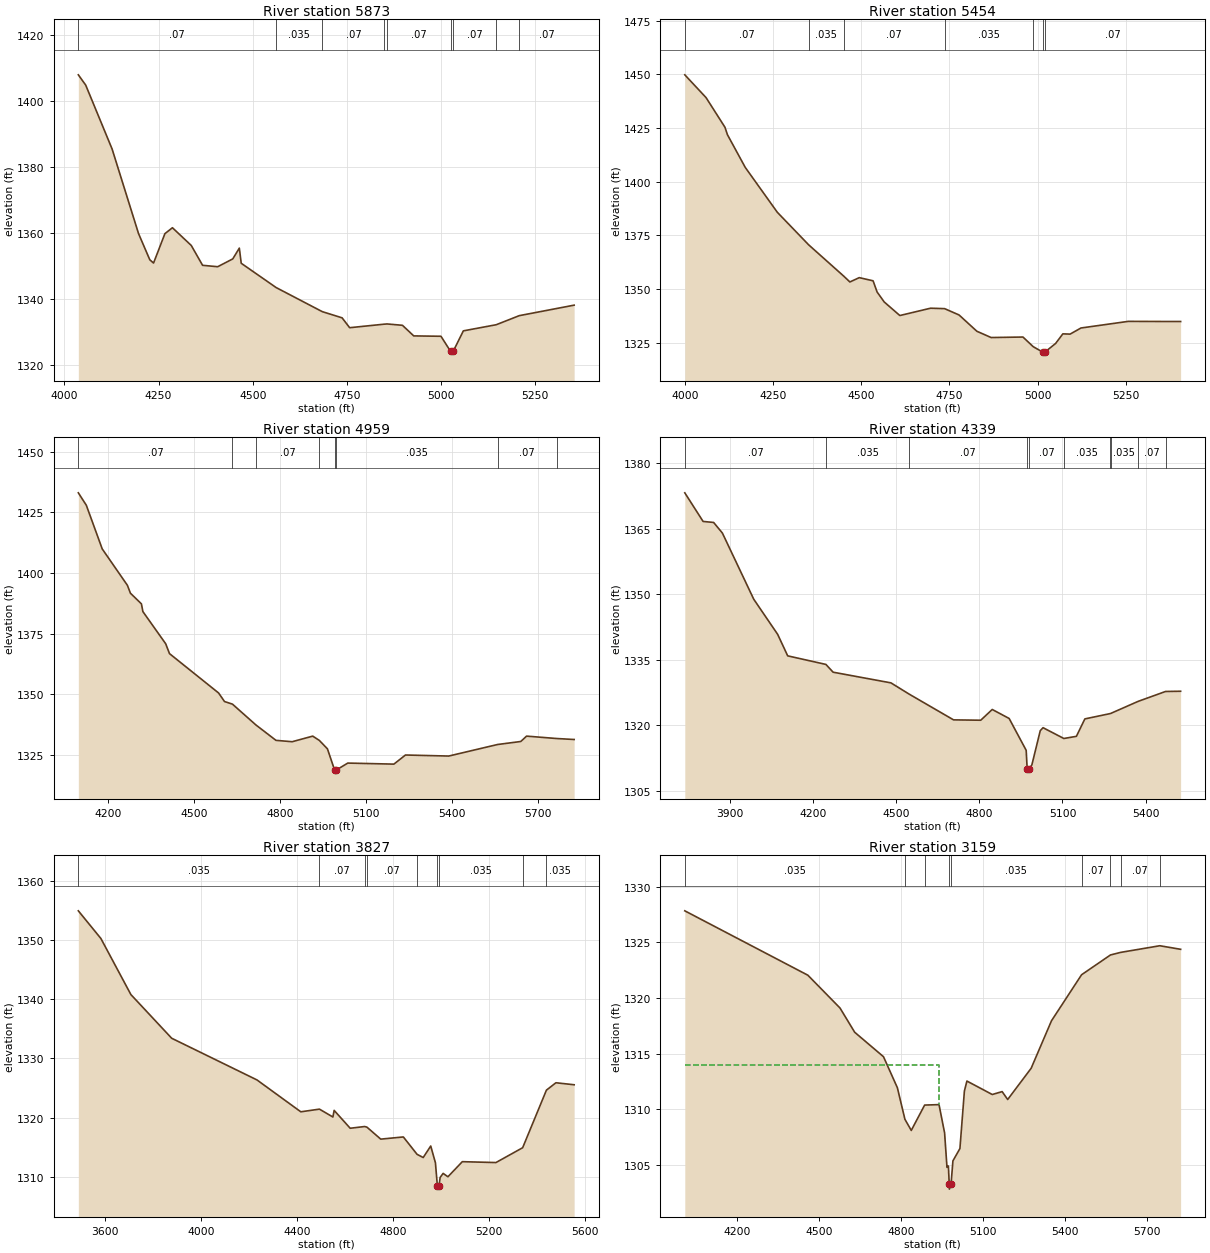
Type RM Length L Ch R = 1 ,5873    ,419,419,419
BEGIN DESCRIPTION:
Chimney Creek 1198 12.0
END DESCRIPTION:
XS GIS Cut Line= 3
      1701485.46      7050835.93      1702447.19      7050784.59
      1702779.22      7050662.68
#Sta/Elev= 30
  4036.9    1408  4056.5 1404.88  4126.6 1385.47  4196.7 1359.82  4226.7 1351.83
  4236.7 1350.84  4266.8 1359.76  4286.8 1361.56  4336.9 1356.17  4366.9 1350.15
    4407 1349.72    4447 1352.09  4464.5 1355.37  4469.5 1350.77  4562.3 1343.39
  4684.7 1336.08  4737.4  1334.2  4757.5  1331.2  4849.8 1332.28  4856.7 1332.34
  4897.7 1331.93  4927.7 1328.71    5000  1328.6  5025.7 1323.98  5026.2 1323.48
  5032.3 1323.98  5059.4 1330.24  5146.9 1332.11  5207.9 1334.86  5353.7 1338.05
#Mann= 9 ,-1 , 0
  4036.9     .07       0  4562.3    .035       0  4684.7     .07       0
  4849.8    .035       0  4856.7     .07       0  5025.7     .07       0
  5032.3     .07       0  5146.9    .035       0  5207.9     .07       0
Bank Sta=5025.7,5032.3
XS Rating Curve= 0 ,0
Exp/Cntr=0.3,0.1

Type RM Length L Ch R = 1 ,5454    ,495,495,495
BEGIN DESCRIPTION:
Chimney Creek 1198 11.0
END DESCRIPTION:
XS GIS Cut Line= 3
      1701315.29      7051017.21       1702305.5      7051158.21
      1702699.31      7051254.91
#Sta/Elev= 30
  3999.8 1449.73  4060.1 1439.12  4113.7 1425.31  4120.7 1421.85  4171.2 1406.63
  4262.1 1385.74    4351 1370.58  4450.7 1355.97  4467.8  1353.3  4494.4 1355.31
  4533.6 1353.84    4545 1348.63  4565.2 1343.98  4609.5 1337.67  4696.5 1341.08
  4736.4 1340.88  4777.3 1337.94  4827.8 1330.36  4868.2 1327.43  4958.5 1327.66
  4987.5 1323.19  5014.2 1320.67  5014.7 1320.17  5020.8 1320.67    5051 1324.65
  5071.6 1329.14  5092.2 1329.02    5123 1331.87  5256.9 1334.95  5405.5 1334.88
#Mann= 7 ,-1 , 0
  3999.8     .07       0    4351    .035       0  4450.7     .07       0
  4736.4    .035       0  4987.5     .07       0  5014.2     .07       0
  5020.8     .07       0
Bank Sta=5014.2,5020.8
XS Rating Curve= 0 ,0
Exp/Cntr=0.3,0.1

Type RM Length L Ch R = 1 ,4959    ,620,620,620
BEGIN DESCRIPTION:
Chimney Creek 1198 10.0
END DESCRIPTION:
XS GIS Cut Line= 3
      1701127.84      7051345.35        1702005.        7051538.
      1702830.03        7051613.
#Sta/Elev= 30
  4097.9 1433.09  4125.7 1427.97  4181.1 1409.95  4268.7 1394.95  4279.3 1391.68
  4317.6 1387.28  4322.7 1384.09  4402.1 1370.82  4415.4 1366.75  4586.4  1350.5
  4606.9 1346.98  4634.6 1345.91  4716.4 1337.31  4786.1 1330.97  4842.4  1330.4
  4914.1 1332.71  4937.1 1330.94  4965.3 1327.47  4990.1 1318.77  4990.6 1318.27
  4996.8 1318.77  5036.1 1321.59  5196.8 1321.16    5237 1324.92  5387.6 1324.49
  5557.6 1329.25  5638.6  1330.5  5658.7 1332.71  5763.8 1331.72  5824.4 1331.32
#Mann= 8 ,-1 , 0
  4097.9     .07       0  4634.6     .16       0  4716.4     .07       0
  4937.1    .035       0  4990.1    .035       0  4996.8    .035       0
  5557.6     .07       0  5763.8    .035       0
Bank Sta=4990.1,4996.8
XS Rating Curve= 0 ,0
Exp/Cntr=0.3,0.1

Type RM Length L Ch R = 1 ,4339    ,512,512,512
BEGIN DESCRIPTION:
Chimney Creek 1198 9.0
END DESCRIPTION:
XS GIS Cut Line= 3
      1701122.59      7051689.09      1702355.25       7051967.9
      1702880.01        7052013.
#Sta/Elev= 30
  3736.2 1373.22  3802.3 1366.67  3840.3 1366.44    3872 1364.01  3985.2 1348.87
  4071.6 1340.83  4107.8 1335.91  4245.8 1333.95  4271.8 1332.17  4480.6 1329.73
  4545.7 1327.18  4706.7 1321.26  4804.9 1321.18  4846.4 1323.64  4907.5 1321.58
    4969 1314.29  4972.6 1310.03  4973.1 1309.53  4979.3 1310.03  4989.5 1310.95
  5019.8 1318.78  5029.9 1319.47    5105    1317  5150.3 1317.49  5180.9 1321.48
  5273.3 1322.71  5273.8 1322.72  5373.1 1325.49  5472.3 1327.76  5526.7 1327.81
#Mann= 10 ,-1 , 0
  3736.2     .07       0  4245.8    .035       0  4545.7     .07       0
  4972.6     .07       0  4979.3     .07       0    5105    .035       0
  5273.3     .07       0  5273.8    .035       0  5373.1     .07       0
  5472.3    .035       0
Bank Sta=4972.6,4979.3
XS Rating Curve= 0 ,0
Exp/Cntr=0.3,0.1

Type RM Length L Ch R = 1 ,3827    ,668,668,668
BEGIN DESCRIPTION:
Chimney Creek 1198 8.0
END DESCRIPTION:
XS GIS Cut Line= 3
      1700924.68       7051944.3      1702375.03      7052368.07
      1702930.89       7052390.3
#Sta/Elev= 30
    3489 1354.96  3583.1 1350.28  3708.1 1340.81  3878.3 1333.42  4233.7 1326.38
  4416.6 1320.99  4494.3 1321.44  4550.4 1320.11  4555.6 1321.23  4622.5 1318.21
  4682.6  1318.5  4692.2  1318.4  4749.9 1316.37  4844.1 1316.74  4901.4  1313.8
    4927 1313.26  4958.3 1315.21  4977.9 1312.37  4986.1 1308.42  4986.6 1307.92
  4992.9 1308.42  4997.4 1309.89    5010 1310.58    5030 1310.01    5090 1312.56
  5230.2 1312.41  5341.6 1314.92  5440.7 1324.65  5480.3  1325.9  5556.3 1325.56
#Mann= 9 ,-1 , 0
    3489    .035       0  4494.3     .07       0  4682.6    .035       0
  4692.2     .07       0  4901.4    .035       0  4986.1    .035       0
  4992.9    .035       0  5341.6     .07       0  5440.7    .035       0
Bank Sta=4986.1,4992.9
XS Rating Curve= 0 ,0
Exp/Cntr=0.3,0.1

Type RM Length L Ch R = 1 ,3159    ,368,368,368
BEGIN DESCRIPTION:
Chimney Creek 1198 7.0
END DESCRIPTION:
XS GIS Cut Line= 3
      1701129.97        7053063.        1702105.        7052888.
      1702880.05      7052612.98
#Sta/Elev= 30
  4009.4 1327.84  4459.4 1322.05  4576.9  1319.1  4630.6 1316.92  4735.9 1314.72
  4786.7 1311.93  4814.3 1309.09  4837.5 1308.09  4886.4 1310.37    4939 1310.41
  4959.4 1307.86  4968.1 1304.77  4973.2 1304.89  4976.3 1303.31  4976.8 1302.81
  4983.1 1303.31  4989.8 1305.35  5015.4 1306.46  5031.8 1311.64    5041 1312.53
  5133.6 1311.32  5169.8 1311.58    5190 1310.87  5275.9 1313.68  5350.2 1317.95
  5460.2 1322.09  5565.9 1323.87  5602.7  1324.1  5746.3  1324.7  5822.4 1324.38
#Mann= 9 ,-1 , 0
  4009.4    .035       0  4814.3     .07       0  4886.4    .035       0
  4976.3    .035       0  4983.1    .035       0  5460.2     .07       0
  5565.9    .035       0  5602.7     .07       0  5746.3    .035       0
#XS Ineff= 2 , 0
       0    4939    1314               0
Permanent Ineff=
       F       F
Bank Sta=4976.3,4983.1
XS Rating Curve= 0 ,0
Exp/Cntr=0.3,0.1

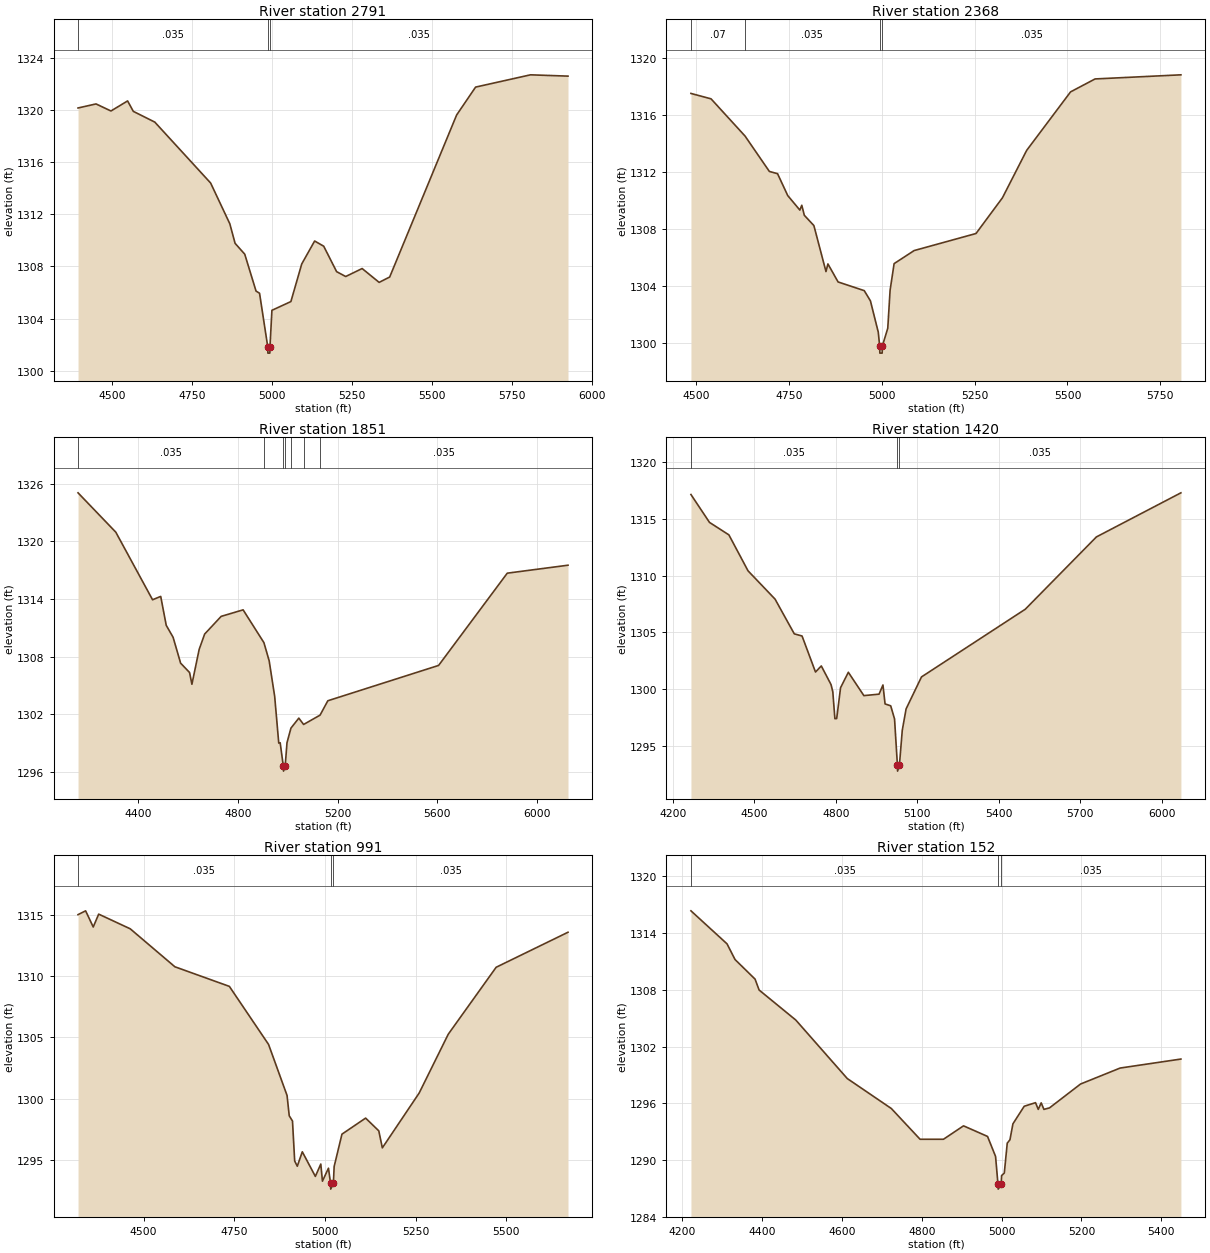
Type RM Length L Ch R = 1 ,2791    ,423,423,423
BEGIN DESCRIPTION:
Chimney Creek 1198 6.0
END DESCRIPTION:
XS GIS Cut Line= 3
      1701595.23      7053484.25      1702150.81      7053239.74
      1702991.37      7052851.24
#Sta/Elev= 30
    4393 1320.14  4449.3 1320.45    4496 1319.91  4548.1 1320.68    4566 1319.88
  4633.1 1319.06  4807.9 1314.39  4867.9 1311.27  4884.4 1309.77  4914.6 1308.94
    4950 1306.11  4960.9 1305.95  4986.5 1301.86    4987 1301.36  4993.1 1301.36
  4993.6 1301.86  4999.6 1304.64    5059 1305.31  5092.9 1308.19  5133.3 1309.95
  5161.7 1309.55  5202.1  1307.6  5230.5 1307.23  5281.9 1307.84  5335.1 1306.78
  5368.1 1307.19  5577.5  1319.6  5636.9 1321.74  5808.8 1322.68    5926 1322.58
#Mann= 3 ,-1 , 0
    4393    .035       0  4986.5    .035       0  4993.6    .035       0
Bank Sta=4986.5,4993.6
XS Rating Curve= 0 ,0
Exp/Cntr=0.3,0.1

Type RM Length L Ch R = 1 ,2368    ,517,517,517
BEGIN DESCRIPTION:
Chimney Creek 1198 5.0
END DESCRIPTION:
XS GIS Cut Line= 3
      1701913.31      7053700.91      1702404.45      7053548.64
       1703150.1      7053243.95
#Sta/Elev= 30
  4485.8 1317.54  4539.9 1317.16  4631.5 1314.54    4697 1312.05  4719.1 1311.89
  4746.5 1310.35  4779.1 1309.33  4784.3 1309.67  4791.2 1308.96  4816.9 1308.24
  4849.5    1305  4854.7 1305.54  4882.1 1304.27  4952.5 1303.66  4969.2 1302.94
  4990.3 1300.74  4994.1 1299.76  4994.6 1299.26  5000.8 1299.26  5001.3 1299.76
  5015.9 1301.01  5022.2 1303.69    5033 1305.56    5087 1306.48  5253.6 1307.68
  5324.7 1310.19    5390 1313.53  5508.3 1317.65  5574.3 1318.56  5805.5 1318.85
#Mann= 4 ,-1 , 0
  4485.8     .07       0  4631.5    .035       0  4994.1    .035       0
  5001.3    .035       0
Bank Sta=4994.1,5001.3
XS Rating Curve= 0 ,0
Exp/Cntr=0.3,0.1

Type RM Length L Ch R = 1 ,1851    ,431,431,431
BEGIN DESCRIPTION:
Chimney Creek 1198 4.0
END DESCRIPTION:
XS GIS Cut Line= 3
      1701460.95      7054329.82        1702205.        7053938.
      1703166.71      7053355.85
#Sta/Elev= 30
  4159.2 1325.06  4310.7 1320.96  4458.1 1313.92  4490.8 1314.27  4512.9 1311.26
  4540.5 1310.01  4570.6 1307.32  4606.6 1306.34  4615.9 1305.12  4645.1 1308.76
  4667.1 1310.35  4733.2 1312.19  4821.3 1312.87  4904.8 1309.45  4925.8 1307.56
  4947.9 1303.85  4964.2 1298.99  4969.9 1299.03  4982.7 1296.57  4983.2 1296.07
  4989.9 1296.57  4997.3 1299.03  5013.1 1300.55  5044.7 1301.59  5063.9 1300.93
  5129.8  1301.9  5161.1  1303.4  5605.3 1307.08  5880.7 1316.69  6124.3 1317.52
#Mann= 7 ,-1 , 0
  4159.2    .035       0  4904.8     .07       0  4982.7     .07       0
  4989.9     .07       0  5013.1    .035       0  5063.9     .07       0
  5129.8    .035       0
Bank Sta=4982.7,4989.9
XS Rating Curve= 0 ,0
Exp/Cntr=0.3,0.1

Type RM Length L Ch R = 1 ,1420    ,429,429,429
BEGIN DESCRIPTION:
Chimney Creek 1198 3.0
END DESCRIPTION:
XS GIS Cut Line= 3
      1701948.19       7054657.4        1702505.        7054188.
      1703238.68       7053401.7
#Sta/Elev= 30
  4267.2 1317.17  4335.5 1314.71  4406.9 1313.61  4477.3 1310.44  4576.9 1307.94
  4647.6 1304.88  4676.2 1304.69  4725.7 1301.51    4747 1302.05  4782.8 1300.41
  4789.4 1299.77  4797.1  1297.4  4803.7 1297.41    4818 1300.13  4846.6 1301.49
  4903.8 1299.43  4959.7 1299.56    4974 1300.37  4981.8  1298.7  5002.6 1298.53
  5016.7 1297.37  5027.3 1293.27  5027.8 1292.77  5034.5 1293.27  5045.1 1296.37
  5059.2 1298.26  5115.9 1301.08  5497.9 1307.05  5759.8 1313.43  6070.9 1317.32
#Mann= 3 ,-1 , 0
  4267.2    .035       0  5027.3    .035       0  5034.5    .035       0
Bank Sta=5027.3,5034.5
XS Rating Curve= 0 ,0
Exp/Cntr=0.3,0.1

Type RM Length L Ch R = 1 ,991     ,839,839,839
BEGIN DESCRIPTION:
Chimney Creek 1198 2.0
END DESCRIPTION:
XS GIS Cut Line= 3
      1702243.31      7054765.05        1702805.        7054388.
      1703385.62      7054046.33
#Sta/Elev= 30
  4319.5 1315.02  4340.4 1315.33  4361.4 1314.01  4376.4 1315.06  4463.4 1313.86
  4586.4 1310.76  4736.5 1309.16  4844.5 1304.42  4895.5 1300.25  4901.5 1298.59
  4910.5 1298.16  4916.5  1294.9  4923.7 1294.47  4937.5 1295.65  4973.5 1293.64
  4988.5 1294.65    4993 1293.25  5009.6 1294.31  5015.3  1293.1  5015.8  1292.6
  5023.2  1293.1  5025.3 1294.45  5046.8 1297.09    5112  1298.4  5148.3 1297.36
  5158.1 1295.97  5259.6 1300.45  5339.7 1305.25  5471.7 1310.72  5669.7 1313.58
#Mann= 3 ,-1 , 0
  4319.5    .035       0  5015.3    .035       0  5023.2    .035       0
Bank Sta=5015.3,5023.2
XS Rating Curve= 0 ,0
Exp/Cntr=0.3,0.1

Type RM Length L Ch R = 1 ,152     ,0,0,0
BEGIN DESCRIPTION:
Chimney Creek 1198 1.0
END DESCRIPTION:
XS GIS Cut Line= 3
      1702355.02        7054838.        1703130.        7054913.
      1703461.17      7054609.05
#Sta/Elev= 30
  4221.4 1316.35  4311.8 1312.86  4331.9  1311.2  4382.1 1309.13  4392.2 1307.98
  4484.3  1304.8  4613.2 1298.62  4723.7 1295.45  4795.7  1292.2  4854.3  1292.2
  4904.6 1293.62  4964.8  1292.5  4984.9 1290.39    4991 1287.43  4991.5 1286.93
    4999 1287.43    5000 1288.36  5006.8 1288.63  5014.2 1291.79    5021 1292.15
  5028.4 1293.83  5056.7 1295.69  5085.1 1296.07  5091.9 1295.36  5099.3 1296.05
  5106.1 1295.36  5120.2 1295.52  5197.9 1298.04  5297.2 1299.73  5449.5 1300.68
#Mann= 3 ,-1 , 0
  4221.4    .035       0    4991    .035       0    4999    .035       0
Bank Sta=4991,4999
XS Rating Curve= 0 ,0
Exp/Cntr=0.3,0.1

Chan Stop Cuts=-1
Use User Specified Reach Order=0
Composite Channel Slope=5