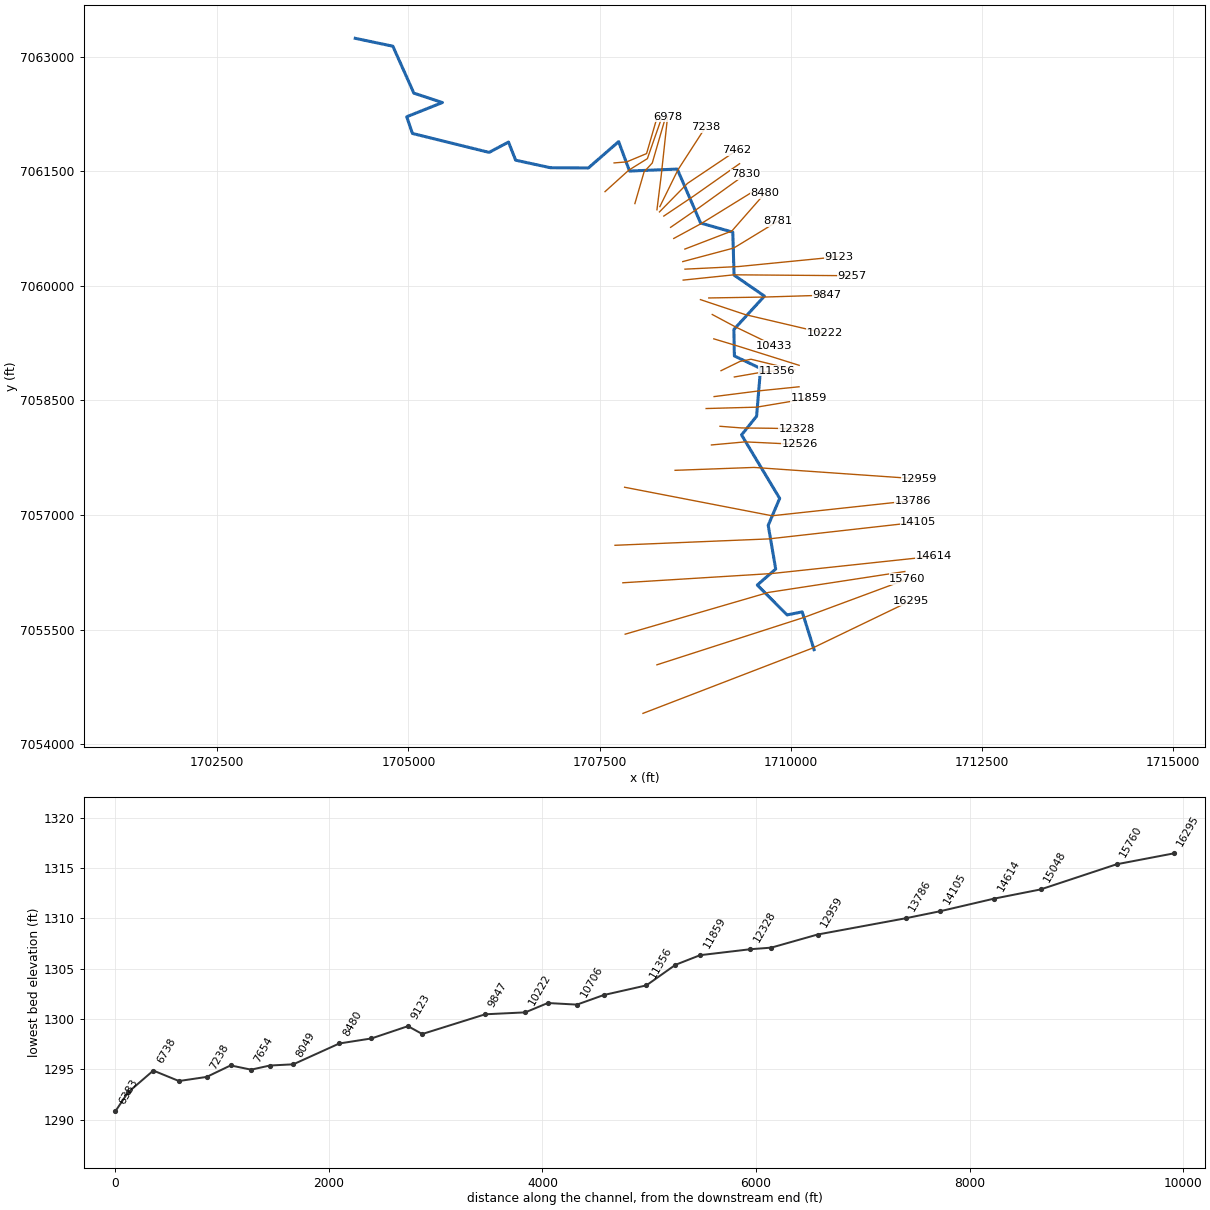
--- Chimney Creek 1199.prj (project) ---

Proj Title=Chimney Creek 1199 Base Level Engineering
Current Plan=p01
Default Exp/Contr=0.3,0.1
English Units
Geom File=g01
Flow File=f01
Plan File=p01
BEGIN DESCRIPTION:
Chimney Creek 1199
END DESCRIPTION:

--- Chimney Creek 1199.p01 (plan) ---

Plan Title=Multiple Run
Short Identifier=Multiple
Geom File=g01
Flow File=f01
Subcritical Flow
K Sum by GR= 0
Std Step Tol= 0.01
Critical Tol= 0.01
Num of Std Step Trials= 20
Max Error Tol= 0.3
Flow Tol Ratio= 0.001
Split Flow NTrial= 30
Split Flow Tol= 0.02
Split Flow Ratio= 0.02
Log Output Level= 0
Friction Slope Method= 1
Unsteady Friction Slope Method= 2
Unsteady Bridges Friction Slope Method= 1
Parabolic Critical Depth
Global Vel Dist=  1 , 1 , 1
Global Log Level= 0
CheckData=True
Encroach Param= -1, 0, 0, 0
BEGIN DESCRIPTION:
Multiple Run
END DESCRIPTION:

--- Chimney Creek 1199.f01 (steady flow) ---

Flow Title=Multiple
Number of Profiles=7
Profile Names=10-year,25-year,50-year,1pct_min,100-year,1pct_plu,500-year
River Rch & RM= Chimney Creek 11,Reach-1,16295
     373     521     646     397     793    1582    1205
River Rch & RM= Chimney Creek 11,Reach-1,15048
     589     842    1057     658    1313    2620    2046
River Rch & RM= Chimney Creek 11,Reach-1,12959
     643     913    1140     705    1407    2807    2164
River Rch & RM= Chimney Creek 11,Reach-1,6978
     721    1023    1277     789    1575    3142    2418
Boundary for River Rch & Prof#=Chimney Creek 11,Reach-1,1
Up Type=0
Dn Type=3
Dn Slope=0.005
Boundary for River Rch & Prof#=Chimney Creek 11,Reach-1,2
Up Type=0
Dn Type=3
Dn Slope=0.005
Boundary for River Rch & Prof#=Chimney Creek 11,Reach-1,3
Up Type=0
Dn Type=3
Dn Slope=0.005
Boundary for River Rch & Prof#=Chimney Creek 11,Reach-1,4
Up Type=0
Dn Type=3
Dn Slope=0.005
Boundary for River Rch & Prof#=Chimney Creek 11,Reach-1,5
Up Type=0
Dn Type=3
Dn Slope=0.005
Boundary for River Rch & Prof#=Chimney Creek 11,Reach-1,6
Up Type=0
Dn Type=3
Dn Slope=0.005
Boundary for River Rch & Prof#=Chimney Creek 11,Reach-1,7
Up Type=0
Dn Type=3
Dn Slope=0.005

--- Chimney Creek 1199.g01 (geometry) ---

Geom Title=Existing Conditions

River Reach=Chimney Creek 11,Reach-1
Reach XY= 30
      1710305.00      7055238.00      1710149.43      7055733.24
      1709952.29      7055693.28      1709562.48      7056084.43
      1709802.95      7056293.84      1709704.90      7056865.31
      1709855.10      7057217.90      1709356.19      7058048.48
      1709552.95      7058293.45      1709605.21      7058918.17
      1709262.48      7059081.94      1709256.09      7059428.37
      1709655.60      7059865.32      1709258.31      7060139.73
      1709241.76      7060701.76      1708821.27      7060820.86
      1708515.32      7061527.17      1707891.36      7061501.43
      1707748.91      7061886.44      1707353.53      7061541.55
      1706855.10      7061545.33      1706402.26      7061643.34
      1706308.70      7061880.35      1706055.01      7061745.53
      1705052.70      7061993.11      1704977.63      7062212.02
      1705444.08      7062397.86      1705071.06      7062520.77
      1704796.69      7063134.91      1704305.00      7063238.00

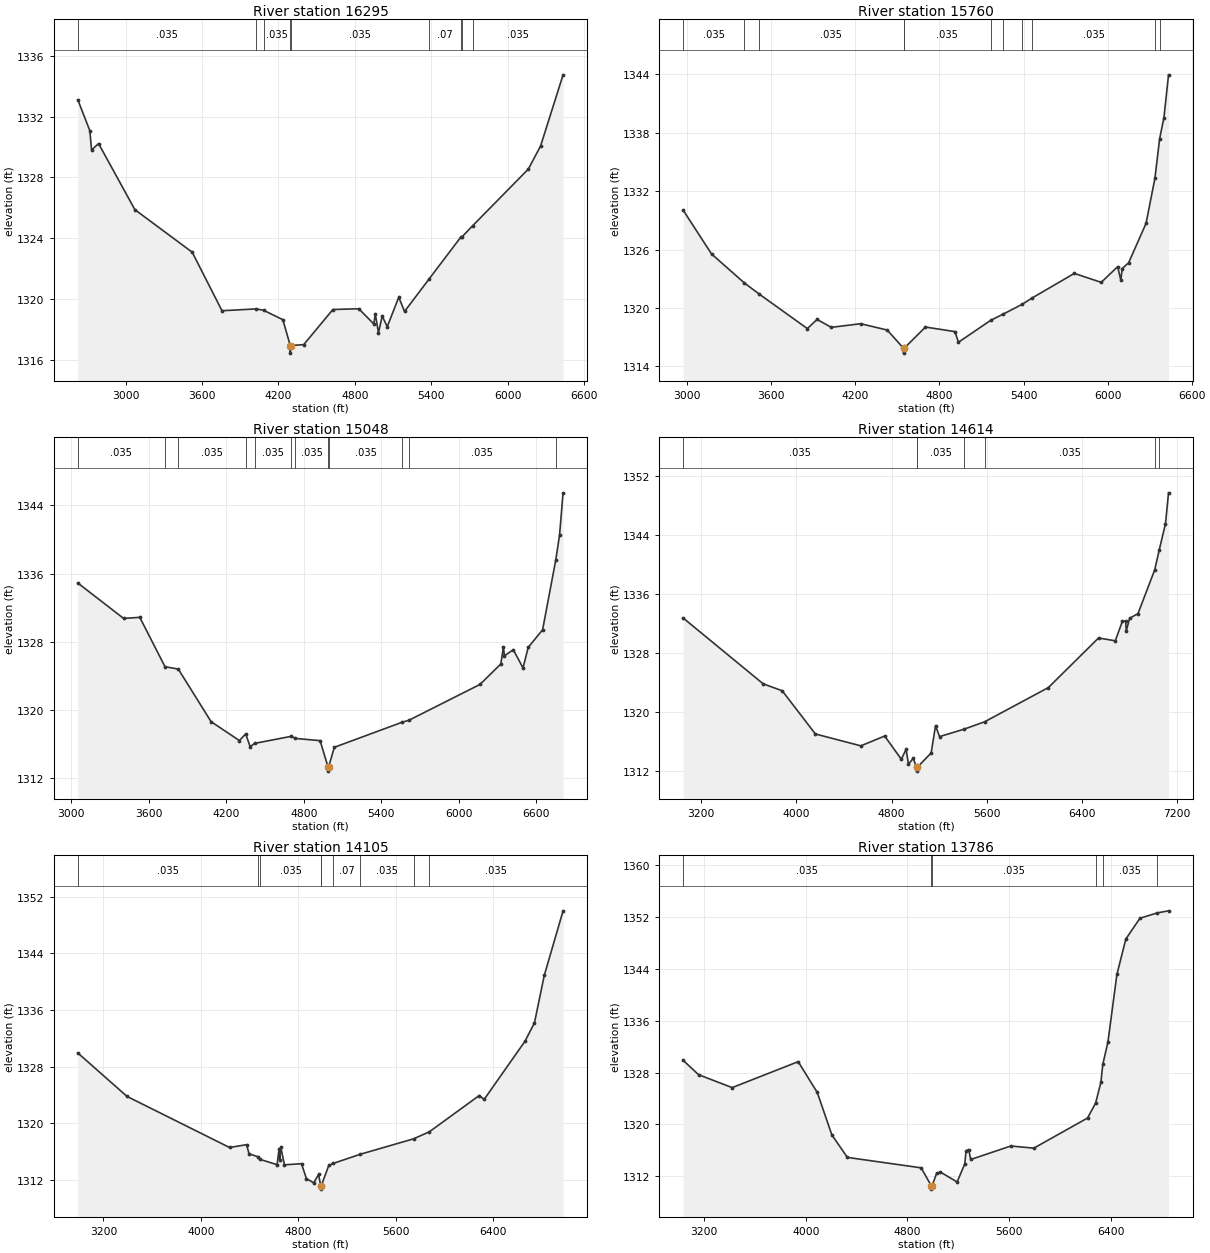
Type RM Length L Ch R = 1,16295,535,535,535
BEGIN DESCRIPTION:
Mapping XS d71f2067
END DESCRIPTION:
XS GIS Cut Line= 3
      1708067.09      7054404.94      1710282.93      7055258.61
      1711574.92      7055881.50
#Sta/Elev= 30
  2625.4 1333.11  2719.6 1331.08  2733.5 1329.80  2788.1 1330.23  3073.3 1325.88
  3523.3 1323.08  3757.1 1319.23  4026.7 1319.35  4083.1 1319.26  4234.7 1318.64
  4292.9 1316.94  4293.2 1316.44  4296.9 1316.94  4398.5 1317.00  4627.6 1319.31
  4830.8 1319.36  4948.6 1318.36  4960.6 1319.02  4985.3 1317.77  5014.5 1318.88
  5054.2 1318.18  5144.7 1320.12  5189.9 1319.18  5381.9 1321.31  5629.6 1324.05
  5642.2 1324.10  5725.6 1324.83  6161.9 1328.55  6257.9 1330.07  6434.3 1334.75
#Mann=9,-1,0
  2625.4   0.035       0  4026.7    0.07       0  4083.1   0.035       0
  4292.9   0.035       0  4296.9   0.035       0  5381.9    0.07       0
  5629.6   0.035       0  5642.2    0.07       0  5725.6   0.035       0
Bank Sta=4292.9,4296.9
Exp/Cntr=0.3,0.1

Type RM Length L Ch R = 1,15760,712,712,712
BEGIN DESCRIPTION:
Mapping XS 44fe2b83
END DESCRIPTION:
XS GIS Cut Line= 3
      1708249.42      7055040.36      1710180.00      7055663.00
      1711525.48      7056162.77
#Sta/Elev= 30
  2971.1 1330.03  3173.3 1325.54  3407.3 1322.57  3510.1 1321.46  3856.8 1317.88
  3926.2 1318.82  4027.7 1318.01  4237.8 1318.38  4427.0 1317.73  4543.6 1315.86
  4543.9 1315.36  4547.6 1315.86  4700.1 1318.04  4910.3 1317.57  4935.5 1316.48
  5165.6 1318.73  5256.6 1319.38  5391.7 1320.39  5463.1 1321.04  5762.3 1323.55
  5954.4 1322.63  6071.7 1324.24  6094.7 1322.84  6103.7 1324.04  6150.0 1324.64
  6274.4 1328.69  6337.8 1333.32  6371.3 1337.38  6402.0 1339.55  6434.9 1343.95
#Mann=11,-1,0
  2971.1   0.035       0  3407.3    0.07       0  3510.1   0.035       0
  4543.6   0.035       0  4547.6   0.035       0  5165.6    0.07       0
  5256.6   0.035       0  5391.7    0.07       0  5463.1   0.035       0
  6337.8    0.07       0  6371.3   0.035       0
Bank Sta=4543.6,4547.6
Exp/Cntr=0.3,0.1

Type RM Length L Ch R = 1,15048,434,434,434
BEGIN DESCRIPTION:
Mapping XS 698ad1d0
END DESCRIPTION:
XS GIS Cut Line= 3
      1707834.48      7055441.19      1709707.69      7055987.63
      1711491.65      7056261.24
#Sta/Elev= 30
  3050.6 1334.89  3405.3 1330.74  3530.3 1330.87  3725.3 1325.09  3828.3 1324.81
  4082.4 1318.65  4301.2 1316.44  4350.3 1317.22  4384.5 1315.72  4419.6 1316.11
  4704.3 1316.94  4734.3 1316.69  4926.2 1316.43  4987.0 1313.36  4987.4 1312.86
  4992.2 1313.36  5035.9 1315.65  5563.4 1318.60  5612.4 1318.81  6163.2 1323.01
  6324.5 1325.40  6344.7 1327.35  6353.2 1326.37  6421.6 1327.08  6496.5 1324.94
  6536.9 1327.35  6648.2 1329.41  6750.9 1337.64  6779.7 1340.54  6806.7 1345.45
#Mann=12,-1,0
  3050.6   0.035       0  3725.3    0.07       0  3828.3   0.035       0
  4350.3    0.07       0  4419.6   0.035       0  4704.3    0.07       0
  4734.3   0.035       0  4987.0   0.035       0  4992.2   0.035       0
  5563.4    0.07       0  5612.4   0.035       0  6750.9    0.07       0
Bank Sta=4987,4992.2
Exp/Cntr=0.3,0.1

Type RM Length L Ch R = 1,14614,509,509,509
BEGIN DESCRIPTION:
Mapping XS f02053f1
END DESCRIPTION:
XS GIS Cut Line= 3
      1707804.13      7056113.93      1709754.87      7056235.03
      1711870.43      7056461.10
#Sta/Elev= 30
  3047.8 1332.71  3720.0 1323.79  3880.3 1322.85  4159.2 1316.99  4541.5 1315.38
  4741.9 1316.71  4882.2 1313.56  4922.3 1314.91  4942.3 1312.89  4982.4 1313.70
  5009.8 1312.45  5010.3 1311.95  5015.1 1312.45  5133.2 1314.42  5169.9 1318.12
  5203.6 1316.63  5413.5 1317.66  5585.2 1318.66  6118.7 1323.28  6541.1 1330.01
  6682.1 1329.63  6742.3 1332.31  6769.4 1332.28  6774.4 1330.96  6802.6 1332.68
  6873.0 1333.32  7013.8 1339.26  7051.5 1341.94  7104.3 1345.52  7129.9 1349.70
#Mann=7,-1,0
  3047.8   0.035       0  5009.8   0.035       0  5015.1   0.035       0
  5413.5    0.07       0  5585.2   0.035       0  7013.8    0.07       0
  7051.5   0.035       0
Bank Sta=5009.8,5015.1
Exp/Cntr=0.3,0.1

Type RM Length L Ch R = 1,14105,319,319,319
BEGIN DESCRIPTION:
Mapping XS a7827055
END DESCRIPTION:
XS GIS Cut Line= 3
      1707701.39      7056604.38      1709712.19      7056687.94
      1711668.40      7056908.20
#Sta/Elev= 30
  2990.3 1329.92  3394.3 1323.78  4235.0 1316.57  4375.1 1316.97  4395.1 1315.68
  4465.2 1315.28  4487.4 1314.88  4625.3 1314.14  4641.7 1316.40  4646.7 1314.87
  4655.3 1316.64  4685.4 1314.12  4825.5 1314.28  4865.5 1312.19  4925.6 1311.57
  4965.6 1312.76  4983.0 1311.19  4983.4 1310.69  4988.3 1311.19  5049.5 1314.05
  5084.2 1314.31  5307.0 1315.61  5744.5 1317.79  5874.6 1318.79  6283.7 1323.91
  6323.9 1323.36  6658.9 1331.57  6736.5 1334.16  6817.0 1340.86  6971.4 1349.99
#Mann=9,-1,0
  2990.3   0.035       0  4465.2    0.07       0  4487.4   0.035       0
  4983.0   0.035       0  4988.3   0.035       0  5084.2    0.07       0
  5307.0   0.035       0  5744.5    0.07       0  5874.6   0.035       0
Bank Sta=4983,4988.3
Exp/Cntr=0.3,0.1

Type RM Length L Ch R = 1,13786,827,827,827
BEGIN DESCRIPTION:
Mapping XS 4f688ce8
END DESCRIPTION:
XS GIS Cut Line= 3
      1707827.22      7057363.93      1709754.94      7056990.67
      1711598.94      7057190.32
#Sta/Elev= 30
  3036.5 1329.88  3156.5 1327.68  3421.3 1325.68  3940.8 1329.69  4091.0 1324.93
  4205.6 1318.38  4327.8 1314.90  4908.4 1313.29  4988.4 1310.50  4988.9 1310.00
  4994.4 1310.50  5030.3 1312.47  5060.4 1312.63  5191.2 1311.11  5251.5 1313.89
  5261.6 1315.90  5281.7 1316.12  5298.6 1314.58  5613.6 1316.66  5794.7 1316.33
  6217.2 1320.98  6280.7 1323.27  6322.5 1326.48  6337.6 1329.27  6378.1 1332.74
  6448.5 1343.16  6518.9 1348.64  6629.6 1351.84  6766.1 1352.67  6854.8 1352.99
#Mann=6,-1,0
  3036.5   0.035       0  4988.4   0.035       0  4994.4   0.035       0
  6280.7    0.07       0  6337.6   0.035       0  6766.1    0.07       0
Bank Sta=4988.4,4994.4
Exp/Cntr=0.3,0.1

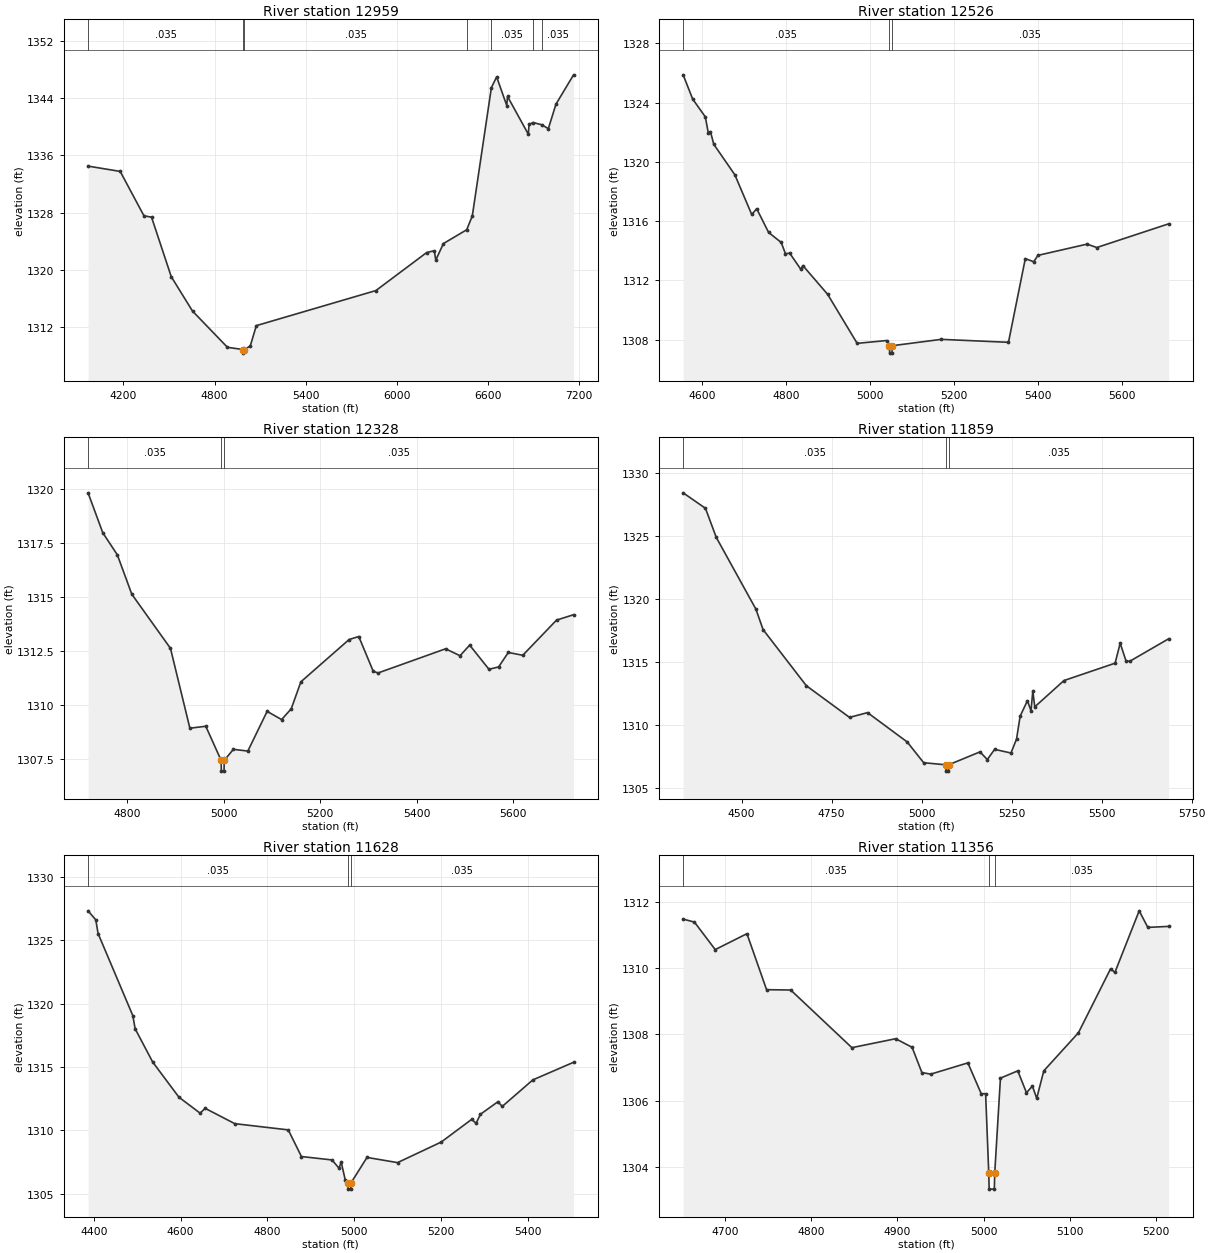
Type RM Length L Ch R = 1,12959,433,433,433
BEGIN DESCRIPTION:
Mapping XS dfda0fe2
END DESCRIPTION:
XS GIS Cut Line= 3
      1708486.94      7057585.28      1709519.48      7057623.19
      1711680.70      7057472.49
#Sta/Elev= 30
  3966.6 1334.50  4178.4 1333.76  4334.9 1327.56  4384.9 1327.37  4515.0 1319.05
  4655.1 1314.25  4885.3 1309.19  4989.3 1308.88  4989.8 1308.38  4995.7 1308.88
  5035.4 1309.36  5075.5 1312.22  5863.8 1317.12  6198.3 1322.43  6248.4 1322.68
  6258.4 1321.38  6308.5 1323.68  6462.0 1325.61  6499.0 1327.54  6624.8 1345.47
  6659.4 1346.96  6726.1 1342.96  6731.1 1344.23  6868.1 1338.96  6873.1 1340.32
  6900.2 1340.59  6957.1 1340.27  7000.2 1339.73  7050.3 1343.15  7166.3 1347.25
#Mann=7,-1,0
  3966.6   0.035       0  4989.3   0.035       0  4995.7   0.035       0
  6462.0    0.07       0  6624.8   0.035       0  6900.2    0.07       0
  6957.1   0.035       0
Bank Sta=4989.3,4995.7
Exp/Cntr=0.3,0.1

Type RM Length L Ch R = 1,12526,198,198,198
BEGIN DESCRIPTION:
Mapping XS fb5d4f8e
END DESCRIPTION:
XS GIS Cut Line= 3
      1708962.37      7057917.35      1709403.81      7057957.72
      1710116.02      7057923.87
#Sta/Elev= 30
  4555.0 1325.87  4577.7 1324.23  4607.8 1323.03  4614.9 1321.94  4620.0 1322.04
  4627.9 1321.18  4678.1 1319.12  4718.3 1316.44  4730.1 1316.83  4758.5 1315.23
  4788.6 1314.55  4798.6 1313.79  4808.7 1313.83  4835.2 1312.74  4840.2 1312.99
  4899.1 1311.05  4969.4 1307.74  5039.5 1307.93  5046.3 1307.58  5046.8 1307.08
  5052.3 1307.08  5052.8 1307.58  5169.7 1308.01  5329.8 1307.81  5369.9 1313.46
  5389.9 1313.25  5399.9 1313.68  5517.0 1314.44  5540.1 1314.21  5711.3 1315.81
#Mann=3,-1,0
  4555.0   0.035       0  5046.3   0.035       0  5052.8   0.035       0
Bank Sta=5046.3,5052.8
Exp/Cntr=0.3,0.1

Type RM Length L Ch R = 1,12328,469,469,469
BEGIN DESCRIPTION:
Mapping XS 84daa186
END DESCRIPTION:
XS GIS Cut Line= 4
      1709074.56      7058161.63      1709355.81      7058139.92
      1709749.91      7058135.58      1710080.31      7058127.78
#Sta/Elev= 30
  4718.9 1319.82  4749.4 1317.97  4779.5 1316.95  4809.6 1315.12  4889.8 1312.61
  4930.0 1308.91  4963.0 1309.00  4994.8 1307.42  4995.3 1306.92  5000.8 1306.92
  5001.3 1307.42  5020.2 1307.93  5050.2 1307.85  5090.2 1309.69  5120.2 1309.31
  5140.2 1309.81  5160.2 1311.06  5260.2 1313.02  5280.2 1313.16  5310.2 1311.55
  5320.2 1311.47  5460.2 1312.59  5490.2 1312.27  5510.2 1312.76  5550.2 1311.64
  5570.2 1311.75  5590.3 1312.42  5620.3 1312.29  5690.3 1313.92  5725.6 1314.17
#Mann=3,-1,0
  4718.9   0.035       0  4994.8   0.035       0  5001.3   0.035       0
Bank Sta=4994.8,5001.3
Exp/Cntr=0.3,0.1

Type RM Length L Ch R = 1,11859,231,231,231
BEGIN DESCRIPTION:
Mapping XS 65472aa5
END DESCRIPTION:
XS GIS Cut Line= 3
      1708893.16      7058393.82      1709554.69      7058411.90
      1710231.66      7058525.47
#Sta/Elev= 30
  4337.9 1328.45  4399.8 1327.22  4429.8 1324.91  4539.8 1319.21  4559.8 1317.58
  4679.9 1313.12  4799.9 1310.60  4849.9 1310.98  4960.0 1308.65  5005.7 1307.00
  5067.9 1306.83  5068.4 1306.33  5074.4 1306.33  5074.9 1306.83  5162.2 1307.86
  5182.5 1307.25  5202.8 1308.06  5248.2 1307.77  5263.6 1308.87  5273.8 1310.71
  5294.0 1311.93  5303.8 1311.12  5308.9 1312.70  5314.3 1311.44  5395.4 1313.53
  5537.4 1314.91  5551.5 1316.50  5567.8 1315.08  5578.0 1315.06  5686.1 1316.85
#Mann=3,-1,0
  4337.9   0.035       0  5067.9   0.035       0  5074.9   0.035       0
Bank Sta=5067.9,5074.9
Exp/Cntr=0.3,0.1

Type RM Length L Ch R = 1,11628,272,272,272
BEGIN DESCRIPTION:
Mapping XS b20e196a
END DESCRIPTION:
XS GIS Cut Line= 3
      1708997.33      7058550.07      1709605.73      7058627.31
      1710108.45      7058678.54
#Sta/Elev= 30
  4386.7 1327.31  4404.5 1326.60  4409.8 1325.52  4489.8 1319.05  4495.2 1318.01
  4535.6 1315.39  4596.0 1312.62  4644.8 1311.36  4656.5 1311.74  4724.8 1310.53
  4848.0 1310.04  4878.3 1307.94  4948.8 1307.67  4964.9 1307.02  4969.9 1307.51
  4979.1 1306.12  4985.7 1305.87  4986.2 1305.37  4992.2 1305.37  4992.7 1305.87
  5029.4 1307.87  5099.8 1307.46  5200.3 1309.08  5270.6 1310.87  5280.7 1310.56
  5290.7 1311.27  5331.0 1312.26  5341.0 1311.89  5411.4 1313.98  5505.3 1315.37
#Mann=3,-1,0
  4386.7   0.035       0  4985.7   0.035       0  4992.7   0.035       0
Bank Sta=4985.7,4992.7
Exp/Cntr=0.3,0.1

Type RM Length L Ch R = 1,11356,400,400,400
BEGIN DESCRIPTION:
Mapping XS 73997636
END DESCRIPTION:
XS GIS Cut Line= 3
      1709262.09      7058806.86      1709605.86      7058866.59
      1709819.03      7058890.20
#Sta/Elev= 30
  4651.4 1311.48  4664.5 1311.39  4688.6 1310.56  4725.4 1311.04  4748.2 1309.35
  4776.2 1309.34  4847.2 1307.60  4898.0 1307.87  4917.1 1307.61  4928.4 1306.85
  4938.6 1306.80  4981.8 1307.14  4997.3 1306.21  5002.4 1306.21  5006.0 1303.83
  5006.5 1303.33  5012.5 1303.33  5013.0 1303.83  5019.6 1306.68  5039.7 1306.90
  5049.8 1306.24  5056.7 1306.44  5061.7 1306.07  5069.9 1306.90  5110.1 1308.05
  5147.4 1309.98  5152.4 1309.87  5180.6 1311.73  5190.6 1311.23  5214.8 1311.26
#Mann=3,-1,0
  4651.4   0.035       0  5006.0   0.035       0  5013.0   0.035       0
Bank Sta=5006,5013
Exp/Cntr=0.3,0.1

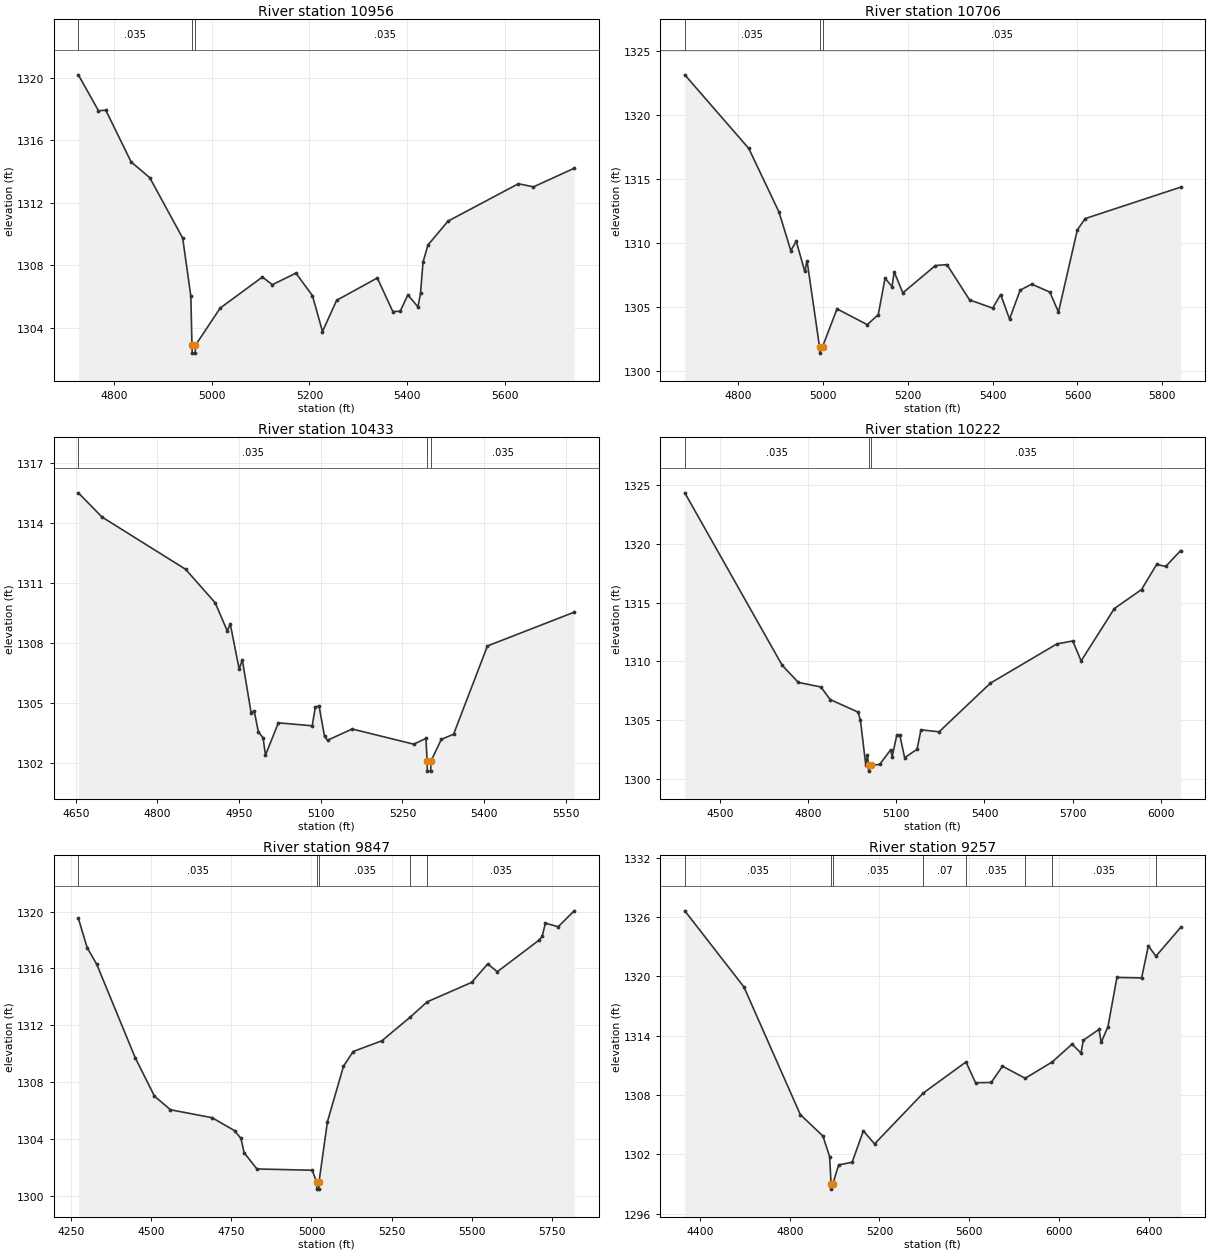
Type RM Length L Ch R = 1,10956,250,250,250
BEGIN DESCRIPTION:
Mapping XS 034f412e
END DESCRIPTION:
XS GIS Cut Line= 4
      1709087.88      7058889.11      1709335.11      7059009.95
      1709479.56      7059039.05      1710055.92      7058898.43
#Sta/Elev= 30
  4726.5 1320.18  4767.8 1317.88  4782.7 1317.92  4834.6 1314.61  4872.8 1313.60
  4940.3 1309.73  4957.0 1306.01  4959.3 1302.87  4959.8 1302.37  4965.9 1302.37
  4966.4 1302.87  5017.0 1305.25  5103.6 1307.24  5124.0 1306.75  5172.3 1307.49
  5206.1 1306.05  5226.7 1303.75  5255.7 1305.75  5339.0 1307.18  5370.8 1305.03
  5385.9 1305.05  5401.7 1306.10  5422.3 1305.33  5427.5 1306.19  5432.7 1308.20
  5442.8 1309.29  5484.0 1310.82  5628.1 1313.21  5659.0 1313.01  5742.3 1314.20
#Mann=3,-1,0
  4726.5   0.035       0  4959.3   0.035       0  4966.4   0.035       0
Bank Sta=4959.3,4966.4
Exp/Cntr=0.3,0.1

Type RM Length L Ch R = 1,10706,273,273,273
BEGIN DESCRIPTION:
Mapping XS 9f127d2a
END DESCRIPTION:
XS GIS Cut Line= 3
      1708993.42      7059305.79      1709305.25      7059212.03
      1710109.74      7058959.19
#Sta/Elev= 30
  4674.3 1323.12  4825.1 1317.38  4896.4 1312.42  4924.2 1309.41  4937.0 1310.14
  4957.2 1307.79  4962.5 1308.62  4991.9 1301.92  4992.4 1301.42  4999.0 1301.92
  5033.2 1304.87  5104.5 1303.64  5130.4 1304.42  5146.4 1307.26  5162.8 1306.61
  5168.0 1307.75  5188.3 1306.12  5265.2 1308.25  5292.4 1308.32  5345.6 1305.57
  5400.1 1304.93  5418.9 1305.99  5439.9 1304.08  5464.9 1306.33  5492.0 1306.80
  5534.9 1306.18  5555.2 1304.62  5599.7 1311.03  5618.1 1311.91  5843.2 1314.36
#Mann=3,-1,0
  4674.3   0.035       0  4991.9   0.035       0  4999.0   0.035       0
Bank Sta=4991.9,4999
Exp/Cntr=0.3,0.1

Type RM Length L Ch R = 1,10433,211,211,211
BEGIN DESCRIPTION:
Mapping XS 6fdd0ee5
END DESCRIPTION:
XS GIS Cut Line= 3
      1708973.19      7059624.28      1709277.84      7059461.52
      1709786.99      7059215.43
#Sta/Elev= 30
  4654.6 1315.52  4698.0 1314.31  4851.7 1311.69  4906.1 1310.01  4928.1 1308.61
  4933.8 1308.94  4950.1 1306.69  4955.8 1307.16  4972.0 1304.51  4977.7 1304.60
  4985.4 1303.54  4994.0 1303.25  4998.4 1302.38  5022.1 1304.00  5084.3 1303.85
  5089.9 1304.78  5096.8 1304.85  5106.9 1303.32  5112.5 1303.13  5157.7 1303.69
  5270.7 1302.93  5293.3 1303.22  5295.3 1302.08  5295.8 1301.58  5301.9 1301.58
  5302.4 1302.08  5321.4 1303.17  5344.0 1303.43  5406.2 1307.85  5565.5 1309.54
#Mann=3,-1,0
  4654.6   0.035       0  5295.3   0.035       0  5302.4   0.035       0
Bank Sta=5295.3,5302.4
Exp/Cntr=0.3,0.1

Type RM Length L Ch R = 1,10222,375,375,375
BEGIN DESCRIPTION:
Mapping XS 06b81344
END DESCRIPTION:
XS GIS Cut Line= 3
      1708818.95      7059819.00      1709405.88      7059622.64
      1710444.36      7059378.46
#Sta/Elev= 30
  4381.1 1324.36  4712.1 1309.67  4767.1 1308.21  4843.7 1307.82  4875.3 1306.75
  4970.0 1305.68  4978.0 1305.03  4996.3 1301.19  5002.1 1302.03  5005.7 1301.15
  5006.2 1300.65  5013.0 1301.15  5043.7 1301.22  5081.0 1302.47  5086.1 1301.88
  5101.8 1303.71  5112.1 1303.72  5128.5 1301.79  5170.9 1302.52  5184.0 1304.17
  5245.6 1304.00  5420.3 1308.15  5646.3 1311.49  5700.1 1311.74  5728.5 1310.04
  5841.5 1314.50  5933.9 1316.12  5985.3 1318.26  6016.1 1318.09  6066.8 1319.44
#Mann=3,-1,0
  4381.1   0.035       0  5005.7   0.035       0  5013.0   0.035       0
Bank Sta=5005.7,5013
Exp/Cntr=0.3,0.1

Type RM Length L Ch R = 1,9847,590,590,590
BEGIN DESCRIPTION:
Mapping XS 4d94dc14
END DESCRIPTION:
XS GIS Cut Line= 3
      1708927.48      7059840.69      1709654.67      7059852.67
      1710474.80      7059877.59
#Sta/Elev= 30
  4272.3 1319.54  4299.8 1317.47  4329.8 1316.29  4449.8 1309.72  4509.9 1307.01
  4559.9 1306.05  4689.9 1305.49  4759.9 1304.58  4779.9 1304.03  4789.9 1303.02
  4829.9 1301.88  5002.3 1301.79  5016.2 1300.96  5016.7 1300.46  5023.1 1300.46
  5023.6 1300.96  5049.9 1305.21  5100.0 1309.11  5130.0 1310.15  5220.0 1310.91
  5308.1 1312.57  5361.3 1313.65  5500.1 1315.02  5550.2 1316.32  5580.2 1315.77
  5710.2 1317.99  5720.2 1318.26  5730.3 1319.19  5770.3 1318.94  5820.1 1320.06
#Mann=5,-1,0
  4272.3   0.035       0  5016.2   0.035       0  5023.6   0.035       0
  5308.1    0.07       0  5361.3   0.035       0
Bank Sta=5016.2,5023.6
Exp/Cntr=0.3,0.1

Type RM Length L Ch R = 1,9257,134,134,134
BEGIN DESCRIPTION:
Mapping XS de689ea9
END DESCRIPTION:
XS GIS Cut Line= 3
      1708593.03      7060074.42      1709257.77      7060143.72
      1710798.78      7060131.71
#Sta/Elev= 30
  4332.5 1326.62  4595.9 1318.93  4847.2 1306.03  4947.8 1303.87  4977.9 1301.79
  4984.3 1299.00  4984.8 1298.50  4991.7 1299.00  5018.1 1300.95  5078.1 1301.21
  5128.1 1304.39  5178.1 1303.07  5395.1 1308.21  5585.5 1311.35  5628.1 1309.25
  5698.1 1309.28  5748.1 1310.92  5849.3 1309.70  5969.7 1311.35  6058.1 1313.15
  6098.1 1312.25  6108.1 1313.54  6178.1 1314.64  6188.1 1313.33  6218.1 1314.92
  6258.1 1319.89  6368.1 1319.84  6398.1 1323.08  6431.9 1322.04  6541.9 1324.94
#Mann=8,-1,0
  4332.5   0.035       0  4984.3   0.035       0  4991.7   0.035       0
  5395.1    0.07       0  5585.5   0.035       0  5849.3    0.07       0
  5969.7   0.035       0  6431.9    0.07       0
Bank Sta=4984.3,4991.7
Exp/Cntr=0.3,0.1

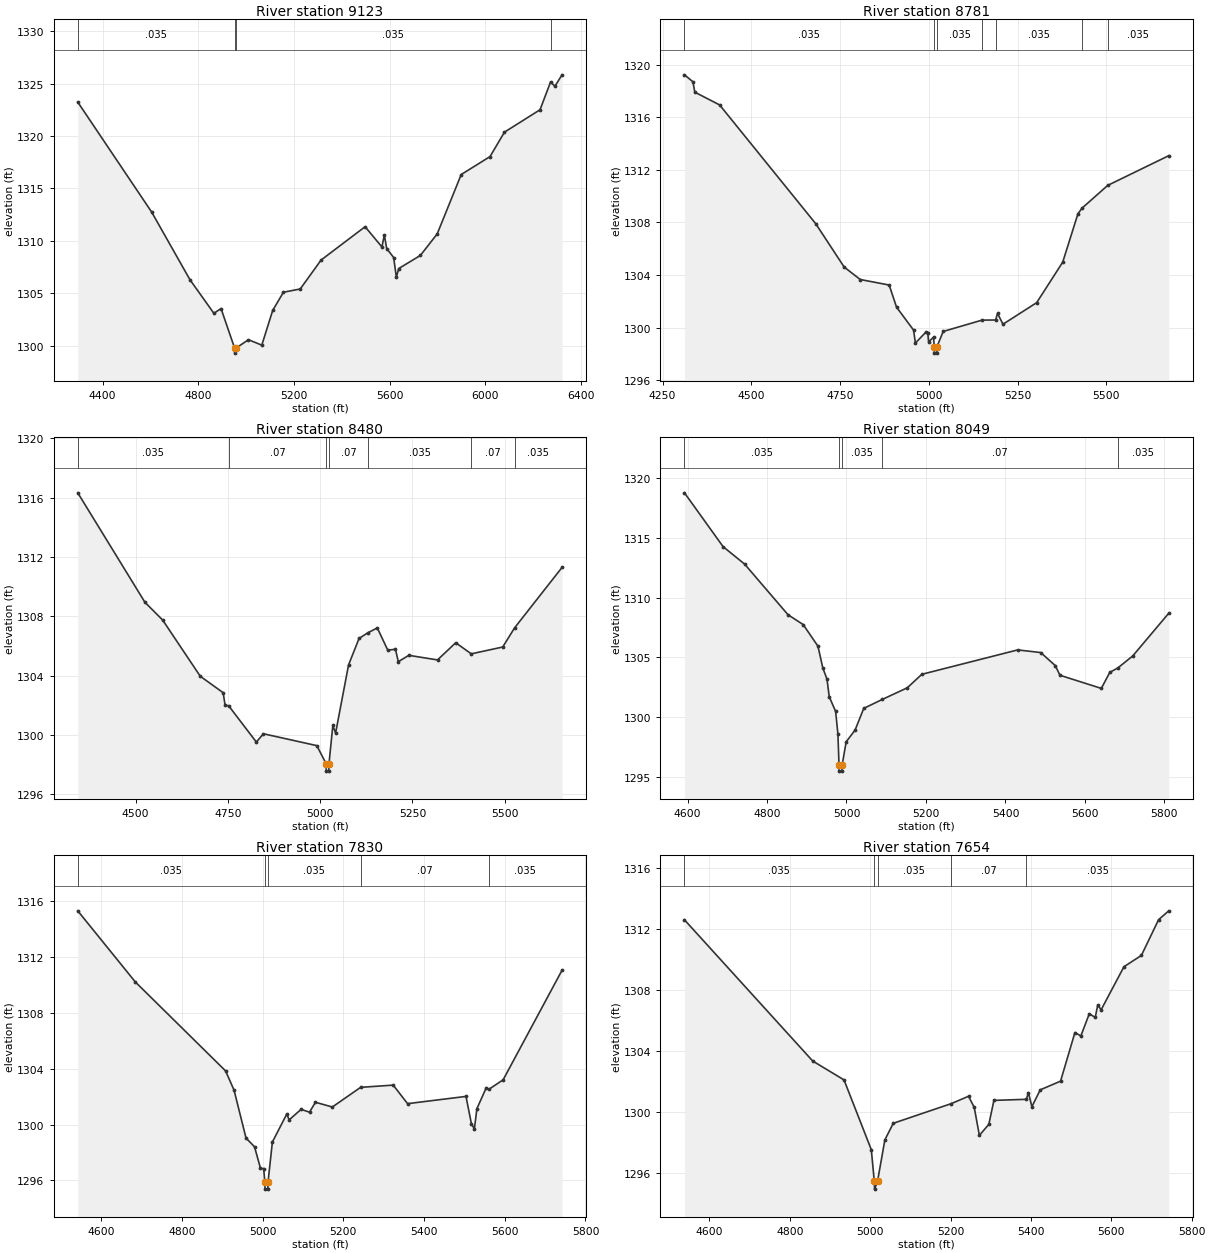
Type RM Length L Ch R = 1,9123,342,342,342
BEGIN DESCRIPTION:
Mapping XS 4da27d76
END DESCRIPTION:
XS GIS Cut Line= 3
      1708616.42      7060217.65      1709319.58      7060252.05
      1710634.70      7060381.71
#Sta/Elev= 30
  4295.9 1323.23  4604.9 1312.74  4765.0 1306.29  4865.2 1303.08  4895.2 1303.53
  4951.6 1299.78  4952.1 1299.28  4959.0 1299.78  5010.0 1300.56  5065.6 1300.04
  5111.2 1303.35  5156.1 1305.09  5226.4 1305.40  5313.6 1308.16  5497.7 1311.34
  5568.1 1309.41  5578.1 1310.54  5588.2 1309.25  5617.2 1308.40  5628.4 1306.52
  5638.4 1307.35  5728.8 1308.60  5799.2 1310.65  5899.7 1316.32  6020.2 1318.03
  6080.5 1320.36  6229.4 1322.50  6273.4 1325.15  6291.6 1324.74  6321.4 1325.83
#Mann=4,-1,0
  4295.9   0.035       0  4951.6   0.035       0  4959.0   0.035       0
  6273.4    0.07       0
Bank Sta=4951.6,4959
Exp/Cntr=0.3,0.1

Type RM Length L Ch R = 1,8781,301,301,301
BEGIN DESCRIPTION:
Mapping XS 82f4a051
END DESCRIPTION:
XS GIS Cut Line= 3
      1708587.78      7060316.60      1709254.26      7060494.07
      1709830.00      7060845.25
#Sta/Elev= 30
  4311.6 1319.23  4335.5 1318.70  4340.7 1317.91  4410.6 1316.94  4681.2 1307.91
  4761.4 1304.61  4806.7 1303.66  4888.2 1303.24  4908.9 1301.56  4956.9 1299.81
  4962.1 1298.83  4991.7 1299.66  4997.0 1299.57  4999.2 1298.92  5013.2 1299.27
  5015.2 1298.56  5015.7 1298.06  5022.5 1298.06  5023.0 1298.56  5040.4 1299.71
  5149.7 1300.57  5188.0 1300.58  5193.4 1301.08  5208.8 1300.26  5303.7 1301.90
  5377.0 1304.98  5419.9 1308.66  5431.5 1309.09  5503.8 1310.82  5675.7 1313.08
#Mann=7,-1,0
  4311.6   0.035       0  5015.2   0.035       0  5023.0   0.035       0
  5149.7    0.07       0  5188.0   0.035       0  5431.5    0.07       0
  5503.8   0.035       0
Bank Sta=5015.2,5023
Exp/Cntr=0.3,0.1

Type RM Length L Ch R = 1,8480,431,431,431
BEGIN DESCRIPTION:
Mapping XS 173cf002
END DESCRIPTION:
XS GIS Cut Line= 3
      1708615.12      7060480.44      1709229.30      7060716.68
      1709660.56      7061208.94
#Sta/Elev= 30
  4343.0 1316.33  4525.0 1308.95  4573.1 1307.75  4675.0 1303.96  4737.0 1302.85
  4742.4 1302.00  4751.9 1301.97  4827.0 1299.52  4846.3 1300.08  4990.9 1299.28
  5016.1 1298.06  5016.6 1297.56  5023.4 1297.56  5023.9 1298.06  5034.3 1300.64
  5041.8 1300.13  5077.0 1304.73  5105.4 1306.51  5129.3 1306.89  5154.8 1307.22
  5183.2 1305.72  5204.1 1305.78  5211.7 1304.94  5240.2 1305.37  5318.0 1305.06
  5367.4 1306.22  5409.4 1305.47  5494.7 1305.93  5527.1 1307.23  5655.5 1311.30
#Mann=7,-1,0
  4343.0   0.035       0  4751.9    0.07       0  5016.1    0.07       0
  5023.9    0.07       0  5129.3   0.035       0  5409.4    0.07       0
  5527.1   0.035       0
Bank Sta=5016.1,5023.9
Exp/Cntr=0.3,0.1

Type RM Length L Ch R = 1,8049,219,219,219
BEGIN DESCRIPTION:
Mapping XS 2b60f996
END DESCRIPTION:
XS GIS Cut Line= 3
      1708469.74      7060619.33      1708828.13      7060813.80
      1709517.93      7061240.00
#Sta/Elev= 30
  4592.3 1318.77  4689.4 1314.27  4743.6 1312.81  4852.9 1308.57  4891.0 1307.75
  4928.2 1305.94  4940.4 1304.12  4950.9 1303.19  4956.6 1301.71  4972.7 1300.48
  4978.4 1298.60  4981.2 1295.99  4981.7 1295.49  4988.5 1295.49  4989.0 1295.99
  4999.2 1297.94  5021.7 1298.93  5043.4 1300.74  5090.3 1301.49  5152.9 1302.46
  5189.6 1303.59  5430.8 1305.63  5488.7 1305.41  5525.3 1304.32  5537.1 1303.51
  5641.2 1302.41  5662.5 1303.75  5682.7 1304.12  5720.4 1305.13  5810.9 1308.70
#Mann=5,-1,0
  4592.3   0.035       0  4981.2   0.035       0  4989.0   0.035       0
  5090.3    0.07       0  5682.7   0.035       0
Bank Sta=4981.2,4989
Exp/Cntr=0.3,0.1

Type RM Length L Ch R = 1,7830,176,176,176
BEGIN DESCRIPTION:
Mapping XS 21a24292
END DESCRIPTION:
XS GIS Cut Line= 3
      1708428.54      7060764.76      1708804.85      7061024.98
      1709407.26      7061459.19
#Sta/Elev= 30
  4541.9 1315.33  4684.5 1310.23  4908.2 1303.85  4929.2 1302.47  4958.9 1299.03
  4979.9 1298.41  4994.7 1296.87  5002.6 1296.84  5005.5 1295.87  5006.0 1295.37
  5012.9 1295.37  5013.4 1295.87  5024.2 1298.75  5059.8 1300.75  5065.9 1300.34
  5095.3 1301.09  5116.2 1300.89  5130.9 1301.60  5172.7 1301.26  5242.9 1302.67
  5323.6 1302.83  5359.2 1301.50  5504.0 1302.02  5517.3 1300.07  5524.8 1299.69
  5531.0 1301.14  5554.3 1302.65  5560.3 1302.52  5596.0 1303.21  5742.0 1311.07
#Mann=5,-1,0
  4541.9   0.035       0  5005.5   0.035       0  5013.4   0.035       0
  5242.9    0.07       0  5560.3   0.035       0
Bank Sta=5005.5,5013.4
Exp/Cntr=0.3,0.1

Type RM Length L Ch R = 1,7654,192,192,192
BEGIN DESCRIPTION:
Mapping XS f530bcad
END DESCRIPTION:
XS GIS Cut Line= 3
      1708339.56      7060912.32      1708723.22      7061169.66
      1709330.64      7061597.61
#Sta/Elev= 30
  4538.0 1312.59  4857.0 1303.35  4935.0 1302.11  5002.9 1297.54  5010.4 1295.46
  5010.9 1294.96  5018.3 1295.46  5036.6 1298.18  5057.5 1299.27  5202.1 1300.56
  5244.8 1301.04  5259.0 1300.31  5271.8 1298.48  5295.3 1299.20  5308.0 1300.77
  5388.8 1300.84  5393.7 1301.28  5402.4 1300.36  5423.3 1301.46  5473.8 1302.03
  5509.5 1305.21  5524.3 1304.99  5545.3 1306.44  5560.1 1306.20  5566.2 1307.00
  5574.9 1306.71  5631.5 1309.52  5674.9 1310.26  5717.7 1312.60  5743.0 1313.18
#Mann=5,-1,0
  4538.0   0.035       0  5010.4   0.035       0  5018.3   0.035       0
  5202.1    0.07       0  5388.8   0.035       0
Bank Sta=5010.4,5018.3
Exp/Cntr=0.3,0.1

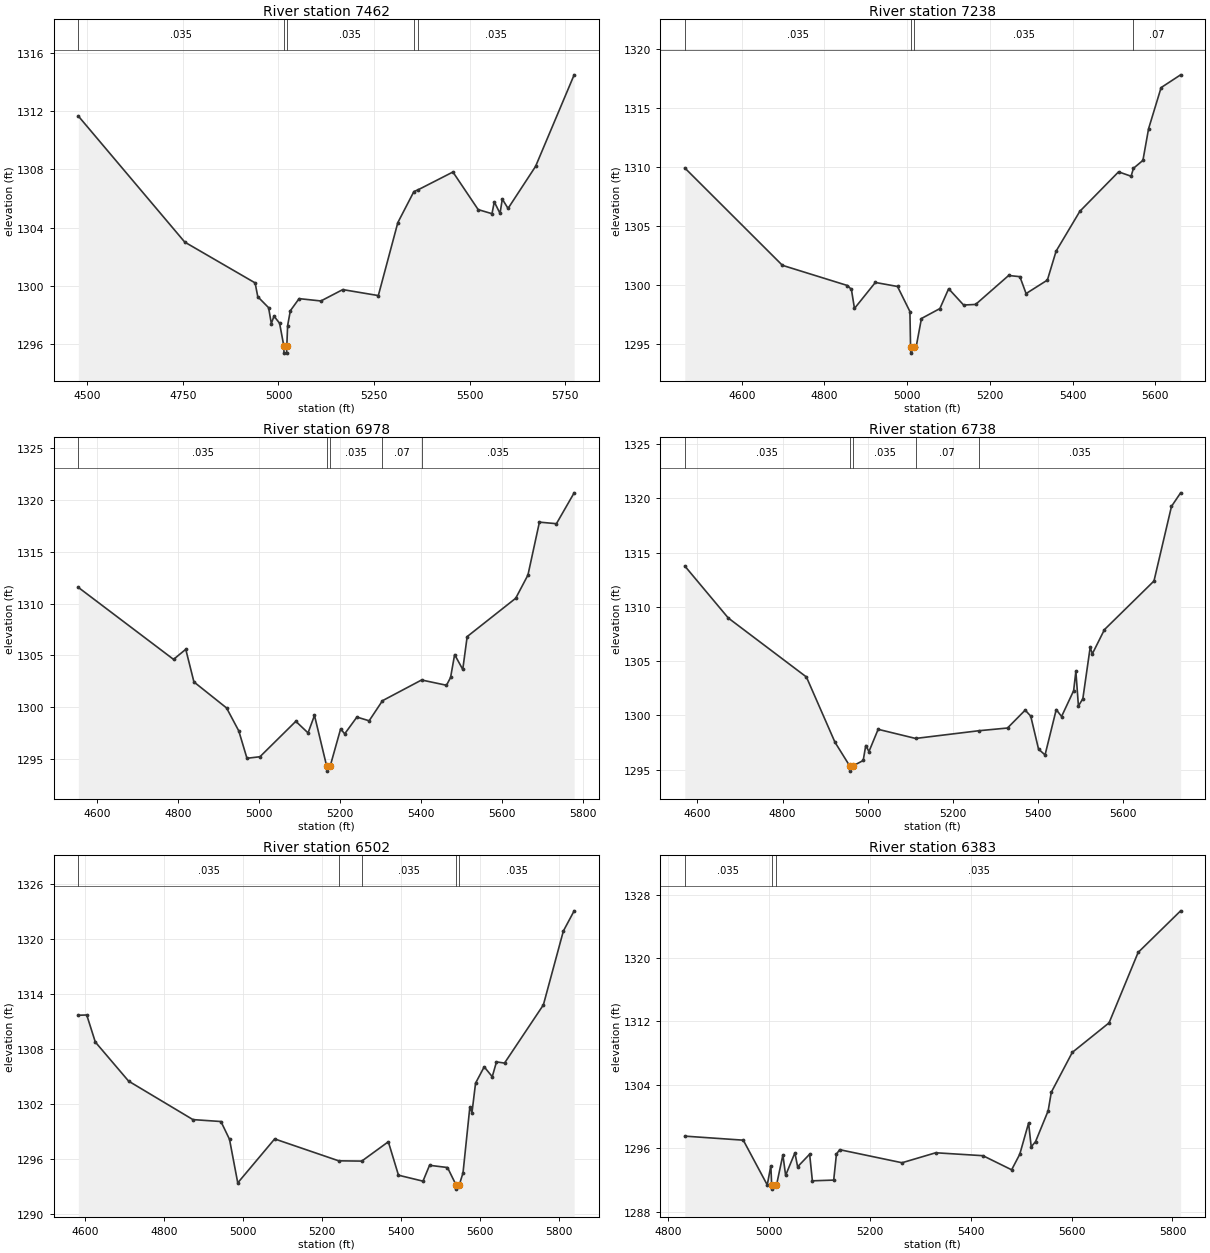
Type RM Length L Ch R = 1,7462,224,224,224
BEGIN DESCRIPTION:
Mapping XS dccc97df
END DESCRIPTION:
XS GIS Cut Line= 3
      1708283.11      7060966.55      1708649.26      7061340.25
      1709291.08      7061770.91
#Sta/Elev= 30
  4476.9 1311.65  4755.1 1303.00  4939.0 1300.20  4946.0 1299.25  4974.2 1298.50
  4981.4 1297.41  4988.4 1297.92  5003.0 1297.43  5014.0 1295.88  5014.5 1295.38
  5021.4 1295.38  5021.9 1295.88  5024.0 1297.27  5031.1 1298.29  5054.0 1299.12
  5111.0 1298.96  5168.1 1299.74  5261.1 1299.33  5312.1 1304.34  5354.1 1306.47
  5365.1 1306.59  5456.1 1307.81  5522.1 1305.23  5558.2 1304.95  5564.2 1305.76
  5579.2 1304.97  5585.2 1305.95  5600.2 1305.31  5672.2 1308.20  5773.0 1314.48
#Mann=5,-1,0
  4476.9   0.035       0  5014.0   0.035       0  5021.9   0.035       0
  5354.1    0.07       0  5365.1   0.035       0
Bank Sta=5014,5021.9
Exp/Cntr=0.3,0.1

Type RM Length L Ch R = 1,7238,260,260,260
BEGIN DESCRIPTION:
Mapping XS 8424ce83
END DESCRIPTION:
XS GIS Cut Line= 3
      1708288.20      7061036.28      1708525.39      7061518.95
      1708884.37      7062074.57
#Sta/Elev= 30
  4462.2 1309.91  4698.3 1301.67  4855.7 1299.96  4865.2 1299.63  4872.6 1298.02
  4923.1 1300.22  4976.7 1299.88  5006.7 1297.76  5008.3 1294.74  5008.8 1294.24
  5016.9 1294.74  5021.8 1294.77  5034.6 1297.17  5079.2 1298.01  5100.4 1299.69
  5136.6 1298.31  5165.6 1298.36  5245.5 1300.81  5272.7 1300.71  5287.7 1299.28
  5339.2 1300.42  5360.3 1302.87  5417.7 1306.24  5511.4 1309.58  5541.7 1309.21
  5547.4 1309.88  5570.3 1310.55  5584.0 1313.23  5614.3 1316.71  5661.5 1317.79
#Mann=4,-1,0
  4462.2   0.035       0  5008.3   0.035       0  5016.9   0.035       0
  5547.4    0.07       0
Bank Sta=5008.3,5016.9
Exp/Cntr=0.3,0.1

Type RM Length L Ch R = 1,6978,240,240,240
BEGIN DESCRIPTION:
Mapping XS 15df0926
END DESCRIPTION:
XS GIS Cut Line= 3
      1708250.00      7060994.61      1708305.43      7061439.86
      1708388.88      7062211.58
#Sta/Elev= 30
  4553.3 1311.57  4788.5 1304.62  4818.7 1305.59  4838.9 1302.44  4919.5 1299.93
  4949.7 1297.71  4969.9 1295.07  5002.0 1295.22  5090.6 1298.64  5120.8 1297.52
  5136.7 1299.21  5166.7 1294.33  5167.2 1293.83  5175.6 1294.33  5201.3 1297.91
  5211.3 1297.43  5241.5 1299.05  5271.7 1298.69  5304.7 1300.63  5401.3 1302.63
  5462.8 1302.12  5472.9 1302.87  5482.9 1305.08  5503.0 1303.65  5513.9 1306.82
  5633.8 1310.52  5664.0 1312.76  5692.4 1317.87  5734.4 1317.72  5778.2 1320.70
#Mann=5,-1,0
  4553.3   0.035       0  5166.7   0.035       0  5175.6   0.035       0
  5304.7    0.07       0  5401.3   0.035       0
Bank Sta=5166.7,5175.6
Exp/Cntr=0.3,0.1

Type RM Length L Ch R = 1,6738,236,236,236
BEGIN DESCRIPTION:
Mapping XS faf901de
END DESCRIPTION:
XS GIS Cut Line= 4
      1707961.36      7061075.49      1708081.85      7061491.01
      1708188.77      7061606.77      1708348.73      7062158.64
#Sta/Elev= 30
  4570.2 1313.76  4672.4 1308.97  4855.9 1303.54  4923.0 1297.53  4957.3 1295.37
  4957.8 1294.87  4966.2 1295.37  4989.3 1295.85  4995.3 1297.23  5002.8 1296.67
  5024.4 1298.72  5112.4 1297.88  5260.9 1298.59  5328.3 1298.84  5369.9 1300.49
  5382.9 1299.93  5401.2 1296.90  5416.5 1296.36  5442.8 1300.54  5455.3 1299.90
  5483.7 1302.28  5488.9 1304.07  5494.9 1300.87  5505.3 1301.54  5522.5 1306.26
  5527.7 1305.68  5556.0 1307.90  5672.4 1312.38  5713.5 1319.25  5735.0 1320.50
#Mann=5,-1,0
  4570.2   0.035       0  4957.3   0.035       0  4966.2   0.035       0
  5112.4    0.07       0  5260.9   0.035       0
Bank Sta=4957.3,4966.2
Exp/Cntr=0.3,0.1

Type RM Length L Ch R = 1,6502,119,119,119
BEGIN DESCRIPTION:
Mapping XS f60e91c4
END DESCRIPTION:
XS GIS Cut Line= 4
      1707570.76      7061231.79      1707881.16      7061512.53
      1708124.77      7061663.84      1708306.76      7062183.81
#Sta/Elev= 30
  4582.8 1311.69  4604.1 1311.72  4625.8 1308.77  4710.2 1304.50  4873.1 1300.30
  4944.1 1300.09  4965.8 1298.15  4986.7 1293.39  5080.2 1298.19  5242.4 1295.80
  5300.9 1295.77  5368.2 1297.88  5393.9 1294.23  5456.0 1293.58  5472.6 1295.31
  5518.1 1295.07  5539.3 1293.21  5539.8 1292.71  5548.2 1293.21  5557.4 1294.48
  5574.8 1301.70  5580.1 1301.06  5589.2 1304.28  5611.1 1306.06  5631.5 1304.98
  5642.2 1306.60  5662.6 1306.47  5761.0 1312.82  5811.7 1320.89  5839.0 1323.09
#Mann=5,-1,0
  4582.8   0.035       0  5242.4    0.07       0  5300.9   0.035       0
  5539.3   0.035       0  5548.2   0.035       0
Bank Sta=5539.3,5548.2
Exp/Cntr=0.3,0.1

Type RM Length L Ch R = 1,6383,246,246,246
BEGIN DESCRIPTION:
Mapping XS 9a532502
END DESCRIPTION:
XS GIS Cut Line= 4
      1707689.52      7061607.68      1707854.77      7061621.56
      1708114.36      7061729.81      1708263.30      7062244.20
#Sta/Elev= 30
  4833.6 1297.52  4949.5 1297.01  4997.0 1291.36  5004.1 1293.77  5005.8 1291.33
  5006.3 1290.83  5015.3 1291.33  5028.0 1295.15  5033.4 1292.57  5051.8 1295.41
  5057.2 1293.65  5081.0 1295.24  5086.4 1291.88  5128.7 1291.97  5134.1 1295.25
  5140.5 1295.81  5264.1 1294.16  5330.9 1295.42  5424.5 1295.05  5481.3 1293.27
  5497.4 1295.23  5514.9 1299.17  5520.1 1296.17  5528.7 1296.83  5553.7 1300.72
  5559.9 1303.06  5601.5 1308.09  5674.4 1311.82  5732.0 1320.71  5816.2 1325.96
#Mann=3,-1,0
  4833.6   0.035       0  5005.8   0.035       0  5015.3   0.035       0
Bank Sta=5005.8,5015.3
Exp/Cntr=0.3,0.1