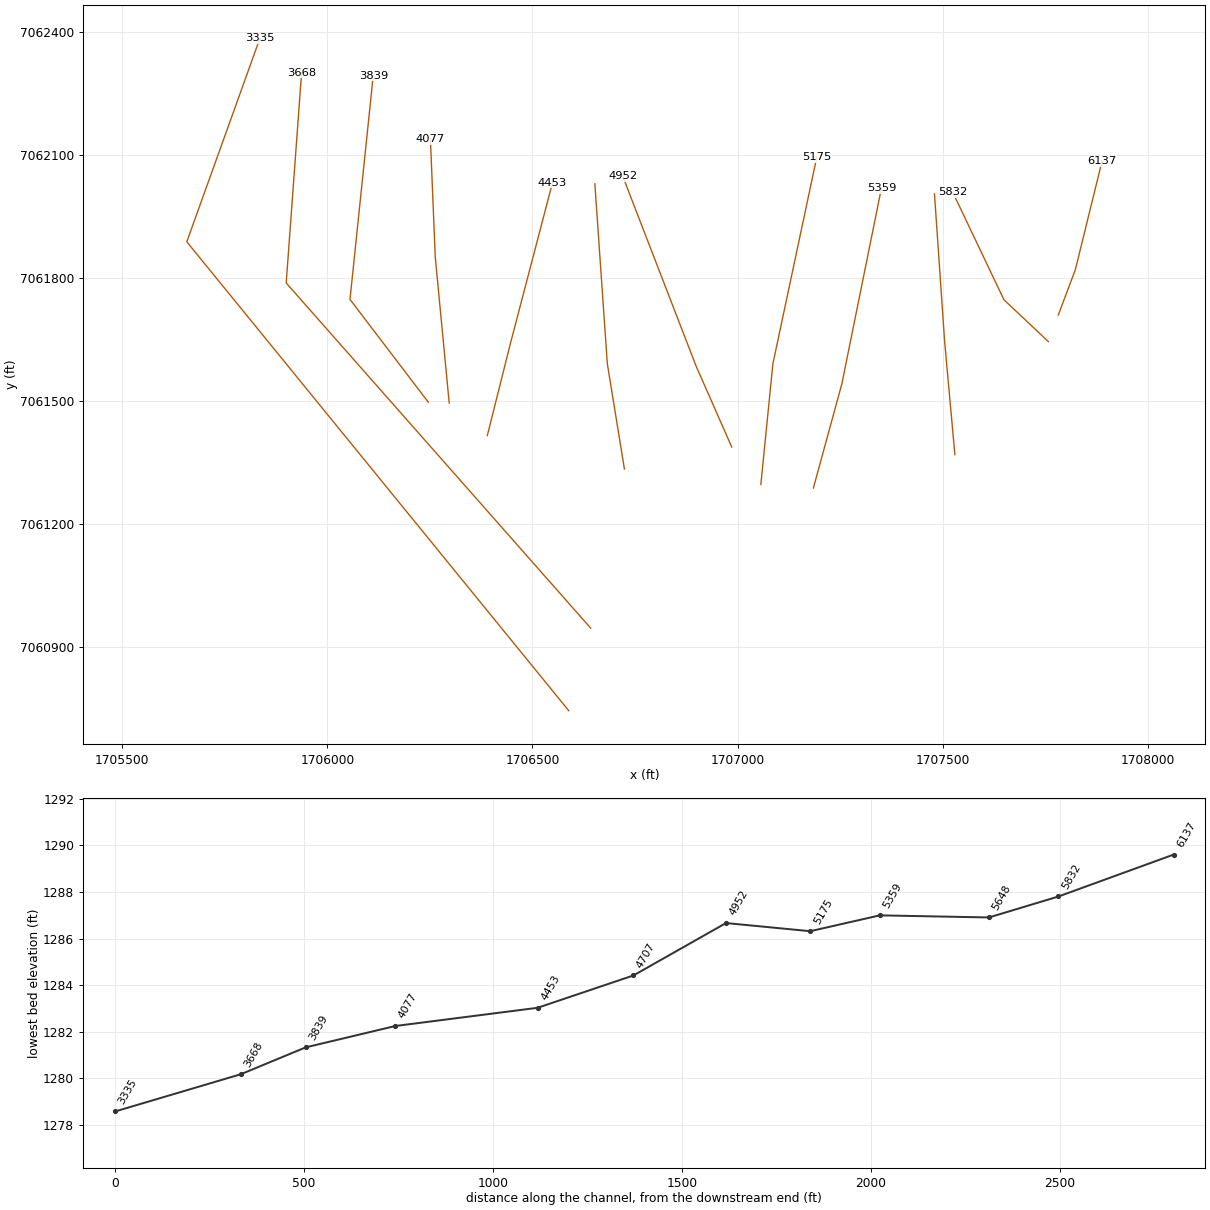
HEC-RAS study Chimney Creek 1199.prj: Chimney Creek 1199 Base Level Engineering

--- Chimney Creek 1199.g01 (geometry) --- (continued)

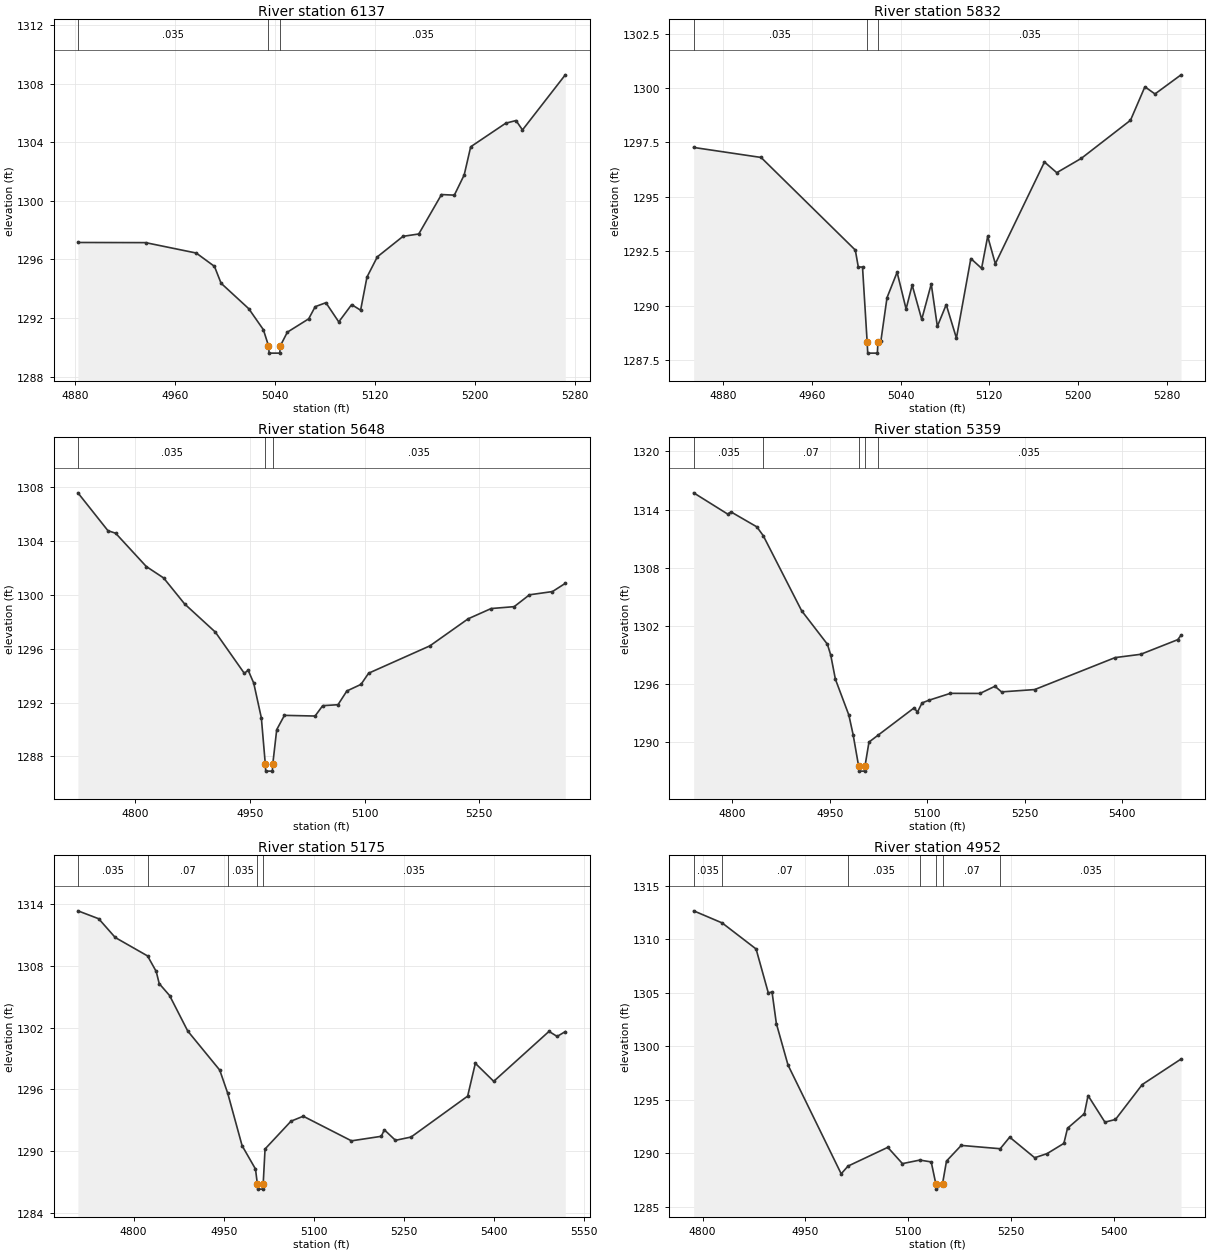
Type RM Length L Ch R = 1,6137,305,305,305
BEGIN DESCRIPTION:
Mapping XS 04e41a55
END DESCRIPTION:
XS GIS Cut Line= 3
      1707782.08      7061709.21      1707823.74      7061820.29
      1707888.70      7062084.28
#Sta/Elev= 30
  4882.0 1297.16  4936.2 1297.15  4976.8 1296.44  4991.4 1295.53  4996.7 1294.38
  5018.9 1292.64  5030.6 1291.21  5034.7 1290.11  5035.2 1289.61  5043.7 1289.61
  5044.2 1290.11  5049.8 1291.04  5066.9 1291.95  5072.1 1292.78  5080.7 1293.05
  5091.0 1291.74  5101.3 1292.92  5108.5 1292.54  5113.6 1294.80  5121.9 1296.18
  5142.5 1297.58  5155.1 1297.74  5173.3 1300.43  5183.6 1300.39  5191.5 1301.77
  5196.7 1303.69  5224.8 1305.30  5233.0 1305.48  5238.2 1304.84  5272.5 1308.60
#Mann=3,-1,0
  4882.0   0.035       0  5034.7   0.035       0  5044.2   0.035       0
Bank Sta=5034.7,5044.2
Exp/Cntr=0.3,0.1

Type RM Length L Ch R = 1,5832,184,184,184
BEGIN DESCRIPTION:
Mapping XS b5b31393
END DESCRIPTION:
XS GIS Cut Line= 3
      1707757.77      7061644.60      1707649.44      7061746.68
      1707524.43      7062009.19
#Sta/Elev= 30
  4853.3 1297.27  4914.1 1296.81  4999.1 1292.55  5001.8 1291.77  5005.6 1291.77
  5009.8 1288.31  5010.3 1287.81  5019.0 1287.81  5019.5 1288.31  5022.2 1288.38
  5027.7 1290.36  5036.8 1291.53  5044.9 1289.84  5050.4 1290.94  5059.0 1289.36
  5067.6 1290.99  5073.1 1289.04  5081.1 1290.04  5090.3 1288.50  5103.3 1292.16
  5113.0 1291.71  5118.5 1293.18  5125.4 1291.92  5169.7 1296.60  5180.8 1296.11
  5203.0 1296.77  5247.3 1298.52  5260.3 1300.06  5269.4 1299.73  5292.9 1300.61
#Mann=3,-1,0
  4853.3   0.035       0  5009.8   0.035       0  5019.5   0.035       0
Bank Sta=5009.8,5019.5
Exp/Cntr=0.3,0.1

Type RM Length L Ch R = 1,5648,289,289,289
BEGIN DESCRIPTION:
Mapping XS afaf86d2
END DESCRIPTION:
XS GIS Cut Line= 3
      1707529.89      7061368.84      1707504.93      7061644.48
      1707480.13      7062004.76
#Sta/Elev= 30
  4724.9 1307.57  4764.2 1304.76  4774.3 1304.57  4814.4 1302.10  4837.1 1301.25
  4864.6 1299.32  4904.8 1297.23  4942.7 1294.17  4947.7 1294.40  4955.0 1293.45
  4965.0 1290.86  4970.2 1287.41  4970.7 1286.91  4979.4 1286.91  4979.9 1287.41
  4985.1 1289.99  4995.2 1291.05  5035.3 1291.00  5045.3 1291.77  5065.3 1291.84
  5076.9 1292.86  5095.4 1293.35  5105.4 1294.18  5185.6 1296.21  5235.7 1298.22
  5265.8 1298.98  5295.9 1299.12  5315.9 1300.00  5346.0 1300.24  5362.8 1300.85
#Mann=3,-1,0
  4724.9   0.035       0  4970.2   0.035       0  4979.9   0.035       0
Bank Sta=4970.2,4979.9
Exp/Cntr=0.3,0.1

Type RM Length L Ch R = 1,5359,184,184,184
BEGIN DESCRIPTION:
Mapping XS ad15397b
END DESCRIPTION:
XS GIS Cut Line= 3
      1707184.85      7061287.52      1707254.28      7061541.40
      1707350.85      7062018.83
#Sta/Elev= 30
  4740.5 1315.73  4792.8 1313.54  4798.0 1313.76  4837.7 1312.22  4847.6 1311.31
  4906.7 1303.56  4946.4 1300.10  4951.5 1298.98  4958.7 1296.49  4979.4 1292.79
  4986.0 1290.76  4994.5 1287.50  4995.0 1287.00  5003.7 1287.00  5004.2 1287.50
  5010.4 1290.00  5023.8 1290.68  5079.9 1293.53  5085.0 1293.09  5092.1 1294.04
  5102.3 1294.31  5135.7 1295.03  5181.3 1295.02  5204.3 1295.76  5214.5 1295.18
  5265.5 1295.42  5389.3 1298.72  5428.7 1299.06  5485.7 1300.57  5490.8 1301.03
#Mann=5,-1,0
  4740.5   0.035       0  4847.6    0.07       0  4994.5    0.07       0
  5004.2    0.07       0  5023.8   0.035       0
Bank Sta=4994.5,5004.2
Exp/Cntr=0.3,0.1

Type RM Length L Ch R = 1,5175,223,223,223
BEGIN DESCRIPTION:
Mapping XS c533c32f
END DESCRIPTION:
XS GIS Cut Line= 3
      1707056.80      7061296.17      1707086.10      7061590.23
      1707193.22      7062094.46
#Sta/Elev= 30
  4707.3 1313.35  4741.9 1312.58  4769.4 1310.76  4823.2 1308.97  4837.6 1307.46
  4842.6 1306.28  4859.9 1305.12  4890.0 1301.68  4943.3 1297.88  4956.7 1295.61
  4980.5 1290.54  5002.8 1288.27  5005.9 1286.82  5006.4 1286.32  5015.1 1286.32
  5015.6 1286.82  5018.7 1290.22  5061.9 1292.92  5082.3 1293.40  5162.5 1291.01
  5212.1 1291.45  5217.2 1292.08  5235.7 1291.06  5261.7 1291.38  5355.8 1295.35
  5368.6 1298.54  5399.2 1296.79  5491.2 1301.64  5504.7 1301.15  5518.3 1301.62
#Mann=5,-1,0
  4707.3   0.035       0  4823.2    0.07       0  4956.7   0.035       0
  5005.9   0.035       0  5015.6   0.035       0
Bank Sta=5005.9,5015.6
Exp/Cntr=0.3,0.1

Type RM Length L Ch R = 1,4952,245,245,245
BEGIN DESCRIPTION:
Mapping XS 7d1cc4b0
END DESCRIPTION:
XS GIS Cut Line= 3
      1706985.78      7061387.57      1706898.99      7061584.59
      1706720.18      7062047.24
#Sta/Elev= 30
  4786.9 1312.64  4828.5 1311.51  4878.0 1309.08  4895.8 1304.99  4901.3 1305.06
  4907.6 1302.12  4924.6 1298.25  5002.2 1288.10  5012.2 1288.82  5070.2 1290.57
  5091.6 1289.05  5116.9 1289.38  5133.6 1289.21  5140.3 1287.17  5140.8 1286.67
  5150.1 1287.17  5155.9 1289.29  5177.4 1290.75  5234.3 1290.44  5248.1 1291.52
  5284.6 1289.60  5302.6 1289.98  5327.2 1290.94  5332.5 1292.35  5357.1 1293.71
  5362.5 1295.40  5387.1 1292.92  5402.5 1293.17  5441.6 1296.43  5498.2 1298.81
#Mann=7,-1,0
  4786.9   0.035       0  4828.5    0.07       0  5012.2   0.035       0
  5116.9    0.07       0  5140.3    0.07       0  5150.1    0.07       0
  5234.3   0.035       0
Bank Sta=5140.3,5150.1
Exp/Cntr=0.3,0.1

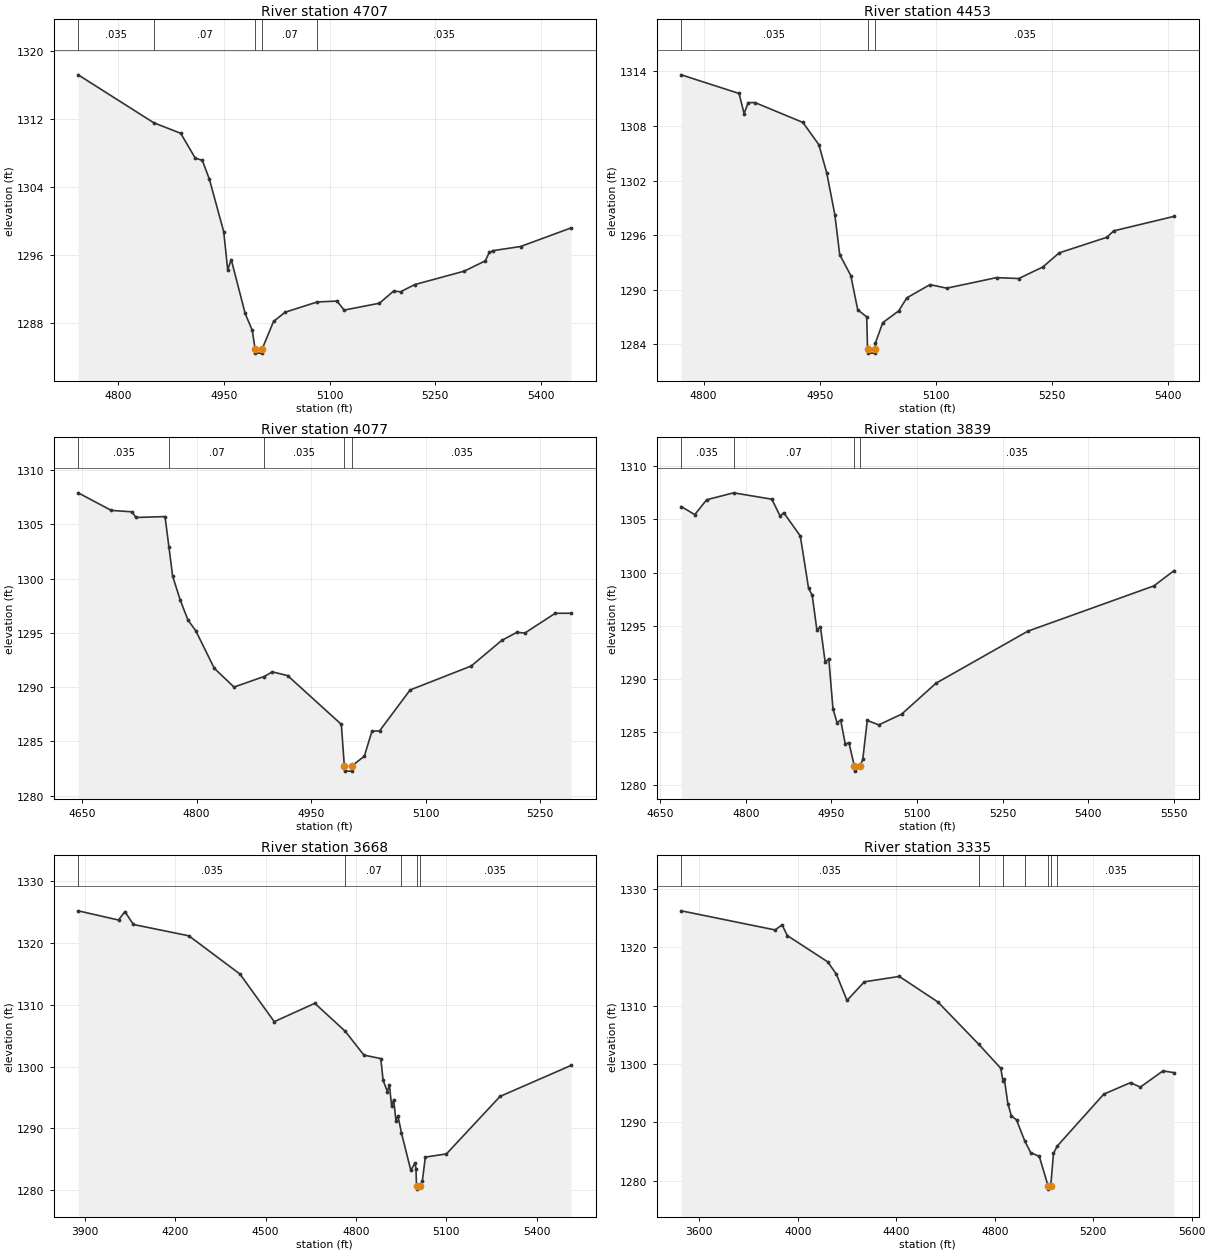
Type RM Length L Ch R = 1,4707,254,254,254
BEGIN DESCRIPTION:
Mapping XS 80689cf6
END DESCRIPTION:
XS GIS Cut Line= 3
      1706724.08      7061333.97      1706682.41      7061590.93
      1706652.03      7062029.27
#Sta/Elev= 30
  4742.9 1317.15  4850.1 1311.52  4888.5 1310.27  4909.1 1307.36  4919.2 1307.09
  4929.3 1304.85  4949.6 1298.69  4955.2 1294.23  4960.3 1295.41  4980.0 1289.09
  4990.1 1287.10  4994.1 1284.92  4994.6 1284.42  5003.7 1284.42  5004.2 1284.92
  5020.3 1288.14  5036.7 1289.23  5082.5 1290.44  5110.5 1290.54  5120.6 1289.48
  5170.7 1290.29  5190.7 1291.71  5200.8 1291.64  5220.8 1292.48  5291.0 1294.06
  5321.0 1295.27  5326.7 1296.27  5331.7 1296.47  5371.2 1296.96  5442.6 1299.14
#Mann=5,-1,0
  4742.9   0.035       0  4850.1    0.07       0  4994.1    0.07       0
  5004.2    0.07       0  5082.5   0.035       0
Bank Sta=4994.1,5004.2
Exp/Cntr=0.3,0.1

Type RM Length L Ch R = 1,4453,376,376,376
BEGIN DESCRIPTION:
Mapping XS d31c9103
END DESCRIPTION:
XS GIS Cut Line= 3
      1706389.87      7061415.58      1706446.30      7061640.40
      1706548.74      7062031.93
#Sta/Elev= 30
  4771.2 1313.62  4845.9 1311.57  4852.4 1309.35  4857.6 1310.56  4866.5 1310.57
  4928.3 1308.39  4949.0 1305.94  4959.3 1302.78  4969.6 1298.25  4975.9 1293.86
  4990.2 1291.56  4999.2 1287.79  5010.8 1287.01  5011.8 1283.53  5012.3 1283.03
  5021.4 1283.03  5021.9 1283.53  5022.0 1284.14  5031.5 1286.38  5052.1 1287.67
  5062.5 1289.10  5092.5 1290.56  5114.2 1290.17  5178.5 1291.33  5207.2 1291.23
  5238.3 1292.50  5259.4 1294.05  5320.9 1295.76  5329.9 1296.47  5407.7 1298.06
#Mann=3,-1,0
  4771.2   0.035       0  5011.8   0.035       0  5021.9   0.035       0
Bank Sta=5011.8,5021.9
Exp/Cntr=0.3,0.1

Type RM Length L Ch R = 1,4077,238,238,238
BEGIN DESCRIPTION:
Mapping XS e12eab5d
END DESCRIPTION:
XS GIS Cut Line= 3
      1706296.90      7061494.76      1706262.88      7061850.99
      1706251.07      7062138.50
#Sta/Elev= 30
  4644.8 1307.90  4688.2 1306.28  4715.4 1306.15  4720.4 1305.63  4758.6 1305.71
  4763.7 1302.91  4768.6 1300.21  4778.6 1298.00  4788.7 1296.17  4798.7 1295.21
  4823.2 1291.72  4849.0 1290.00  4888.4 1290.97  4899.2 1291.40  4919.3 1291.05
  4989.6 1286.56  4993.5 1282.75  4994.0 1282.25  5003.2 1282.25  5003.7 1282.75
  5019.7 1283.62  5029.7 1285.93  5039.7 1285.96  5079.7 1289.73  5159.8 1291.94
  5199.8 1294.30  5219.8 1295.05  5229.9 1294.97  5269.9 1296.80  5290.4 1296.80
#Mann=5,-1,0
  4644.8   0.035       0  4763.7    0.07       0  4888.4   0.035       0
  4993.5   0.035       0  5003.7   0.035       0
Bank Sta=4993.5,5003.7
Exp/Cntr=0.3,0.1

Type RM Length L Ch R = 1,3839,171,171,171
BEGIN DESCRIPTION:
Mapping XS 9d2b5970
END DESCRIPTION:
XS GIS Cut Line= 3
      1706246.19      7061496.47      1706054.98      7061747.31
      1706111.63      7062292.97
#Sta/Elev= 30
  4686.6 1306.21  4710.3 1305.45  4731.2 1306.85  4778.4 1307.50  4845.5 1306.90
  4860.0 1305.31  4866.3 1305.63  4895.4 1303.44  4909.9 1298.51  4916.2 1297.88
  4924.4 1294.62  4930.7 1294.88  4939.0 1291.57  4945.3 1291.90  4952.6 1287.21
  4959.8 1285.88  4966.1 1286.14  4974.3 1283.86  4980.6 1284.02  4990.0 1281.83
  4990.5 1281.33  5000.3 1281.83  5004.9 1282.44  5012.8 1286.10  5032.9 1285.68
  5073.1 1286.69  5133.4 1289.60  5294.3 1294.49  5515.4 1298.75  5550.6 1300.18
#Mann=4,-1,0
  4686.6   0.035       0  4778.4    0.07       0  4990.0    0.07       0
  5000.3   0.035       0
Bank Sta=4990,5000.3
Exp/Cntr=0.3,0.1

Type RM Length L Ch R = 1,3668,333,333,333
BEGIN DESCRIPTION:
Mapping XS 1ac9e8f7
END DESCRIPTION:
XS GIS Cut Line= 3
      1706641.84      7060946.02      1705899.45      7061787.42
      1705937.00      7062300.15
#Sta/Elev= 30
  3877.9 1325.20  4012.0 1323.71  4032.9 1325.08  4061.3 1322.99  4245.4 1321.16
  4415.2 1314.97  4529.0 1307.27  4663.7 1310.24  4764.8 1305.71  4826.8 1301.86
  4882.8 1301.30  4890.4 1297.79  4904.6 1295.97  4911.3 1297.06  4918.8 1293.61
  4925.5 1294.67  4933.1 1291.26  4939.7 1292.04  4951.4 1289.26  4982.4 1283.23
  4996.6 1284.41  4999.6 1283.45  5001.4 1280.68  5001.9 1280.18  5011.7 1280.68
  5020.6 1281.43  5030.7 1285.36  5100.8 1285.88  5278.8 1295.18  5514.1 1300.18
#Mann=5,-1,0
  3877.9   0.035       0  4764.8    0.07       0  4951.4   0.035       0
  5001.4   0.035       0  5011.7   0.035       0
Bank Sta=5001.4,5011.7
Exp/Cntr=0.3,0.1

Type RM Length L Ch R = 1,3335,0,0,0
BEGIN DESCRIPTION:
Mapping XS ebac99dc
END DESCRIPTION:
XS GIS Cut Line= 3
      1706588.48      7060744.62      1705657.08      7061887.82
      1705835.46      7062384.15
#Sta/Elev= 30
  3526.2 1326.22  3907.4 1322.95  3936.1 1323.82  3957.0 1321.99  4121.4 1317.48
  4156.6 1315.37  4199.7 1310.88  4270.1 1314.07  4412.3 1314.99  4568.8 1310.62
  4734.8 1303.38  4824.5 1299.27  4833.0 1297.16  4838.8 1297.48  4853.2 1293.22
  4867.5 1291.12  4888.4 1290.43  4921.4 1286.88  4945.8 1284.84  4981.0 1284.18
  5017.0 1279.08  5017.5 1278.58  5027.4 1279.08  5038.6 1284.70  5053.7 1285.94
  5243.0 1294.84  5351.6 1296.81  5391.3 1296.04  5483.5 1298.82  5528.2 1298.52
#Mann=7,-1,0
  3526.2   0.035       0  4734.8    0.07       0  4833.0   0.035       0
  4921.4    0.07       0  5017.0    0.07       0  5027.4    0.07       0
  5053.7   0.035       0
Bank Sta=5017,5027.4
Exp/Cntr=0.3,0.1

Chan Stop Cuts=-1