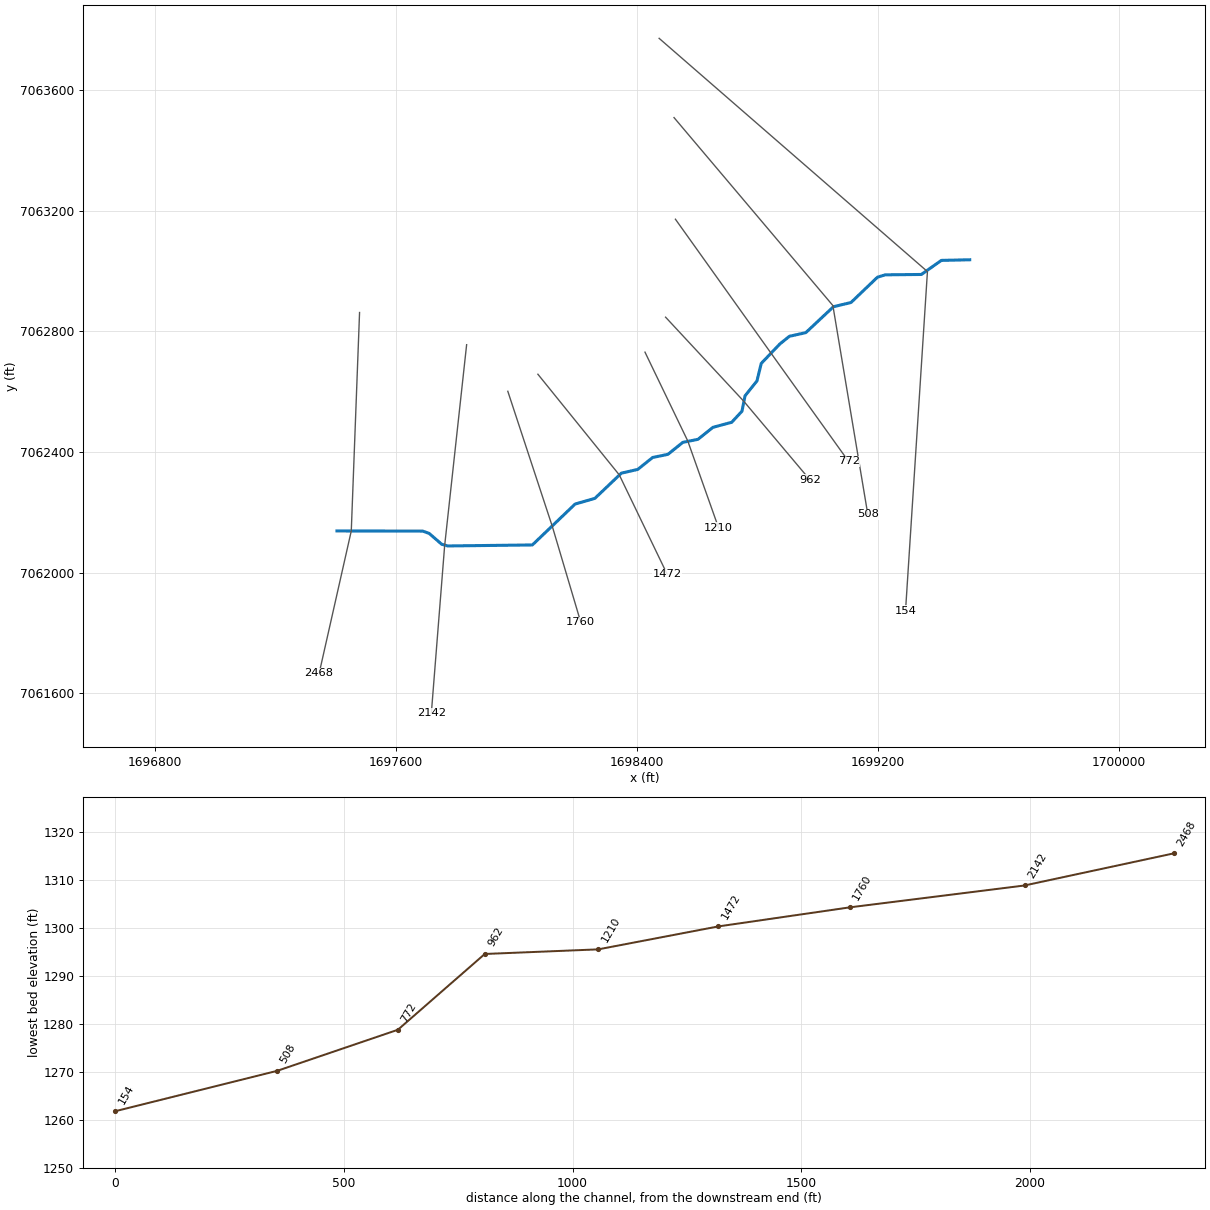
--- Chimney Creek 1200.prj (project) ---

Proj Title=Chimney Creek 1200 Base Level Engineering
Current Plan=p01
Default Exp/Contr=0.3,0.1
English Units
Geom File=g01
Flow File=f01
Plan File=p01
BEGIN DESCRIPTION:
Chimney Creek 1200
END DESCRIPTION:

--- Chimney Creek 1200.p01 (plan) ---

Plan Title=Multiple Run
Short Identifier=Multiple
Geom File=g01
Flow File=f01
Subcritical Flow
K Sum by GR= 0
Std Step Tol= 0.01
Critical Tol= 0.01
Num of Std Step Trials= 20
Max Error Tol= 0.3
Flow Tol Ratio= 0.001
Split Flow NTrial= 30
Split Flow Tol= 0.02
Split Flow Ratio= 0.02
Log Output Level= 0
Friction Slope Method= 1
Unsteady Friction Slope Method= 2
Unsteady Bridges Friction Slope Method= 1
Parabolic Critical Depth
Global Vel Dist=  1 , 1 , 1
Global Log Level= 0
CheckData=True
Encroach Param= -1, 0, 0, 0
BEGIN DESCRIPTION:
Multiple Run
END DESCRIPTION:

--- Chimney Creek 1200.f01 (steady flow) ---

Flow Title=Multiple
Number of Profiles=7
Profile Names=10-year,25-year,50-year,1pct_min,100-year,1pct_plu,500-year
River Rch & RM= Chimney Creek 12,Reach-1,2468
     486     698     881     553    1103    2201    1744
River Rch & RM= Chimney Creek 12,Reach-1,1760
     572     829    1051     663    1322    2638    2111
Boundary for River Rch & Prof#=Chimney Creek 12,Reach-1,1
Up Type=0
Dn Type=3
Dn Slope=0.005
Boundary for River Rch & Prof#=Chimney Creek 12,Reach-1,2
Up Type=0
Dn Type=3
Dn Slope=0.005
Boundary for River Rch & Prof#=Chimney Creek 12,Reach-1,3
Up Type=0
Dn Type=3
Dn Slope=0.005
Boundary for River Rch & Prof#=Chimney Creek 12,Reach-1,4
Up Type=0
Dn Type=3
Dn Slope=0.005
Boundary for River Rch & Prof#=Chimney Creek 12,Reach-1,5
Up Type=0
Dn Type=3
Dn Slope=0.005
Boundary for River Rch & Prof#=Chimney Creek 12,Reach-1,6
Up Type=0
Dn Type=3
Dn Slope=0.005
Boundary for River Rch & Prof#=Chimney Creek 12,Reach-1,7
Up Type=0
Dn Type=3
Dn Slope=0.005

--- Chimney Creek 1200.g01 (geometry) ---

Geom Title=Existing Conditions

River Reach=Chimney Creek 12,Reach-1
Reach XY= 30
      1697405.00      7062138.00      1697689.78      7062137.48
      1697711.06      7062129.86      1697752.67      7062093.75
      1697773.27      7062088.21      1698053.54      7062091.54
      1698195.32      7062227.22      1698261.04      7062246.18
      1698348.95      7062329.84      1698403.26      7062342.19
      1698452.80      7062381.92      1698503.28      7062392.16
      1698552.80      7062431.92      1698603.28      7062442.16
      1698652.84      7062481.89      1698715.00      7062498.63
      1698749.27      7062535.45      1698759.20      7062586.24
      1698798.90      7062635.81      1698813.13      7062694.07
      1698874.77      7062758.42      1698906.64      7062784.03
      1698961.04      7062796.18      1699052.72      7062882.13
      1699111.04      7062896.18      1699198.82      7062980.17
      1699224.99      7062988.02      1699344.50      7062989.21
      1699410.87      7063035.90      1699505.00      7063038.00

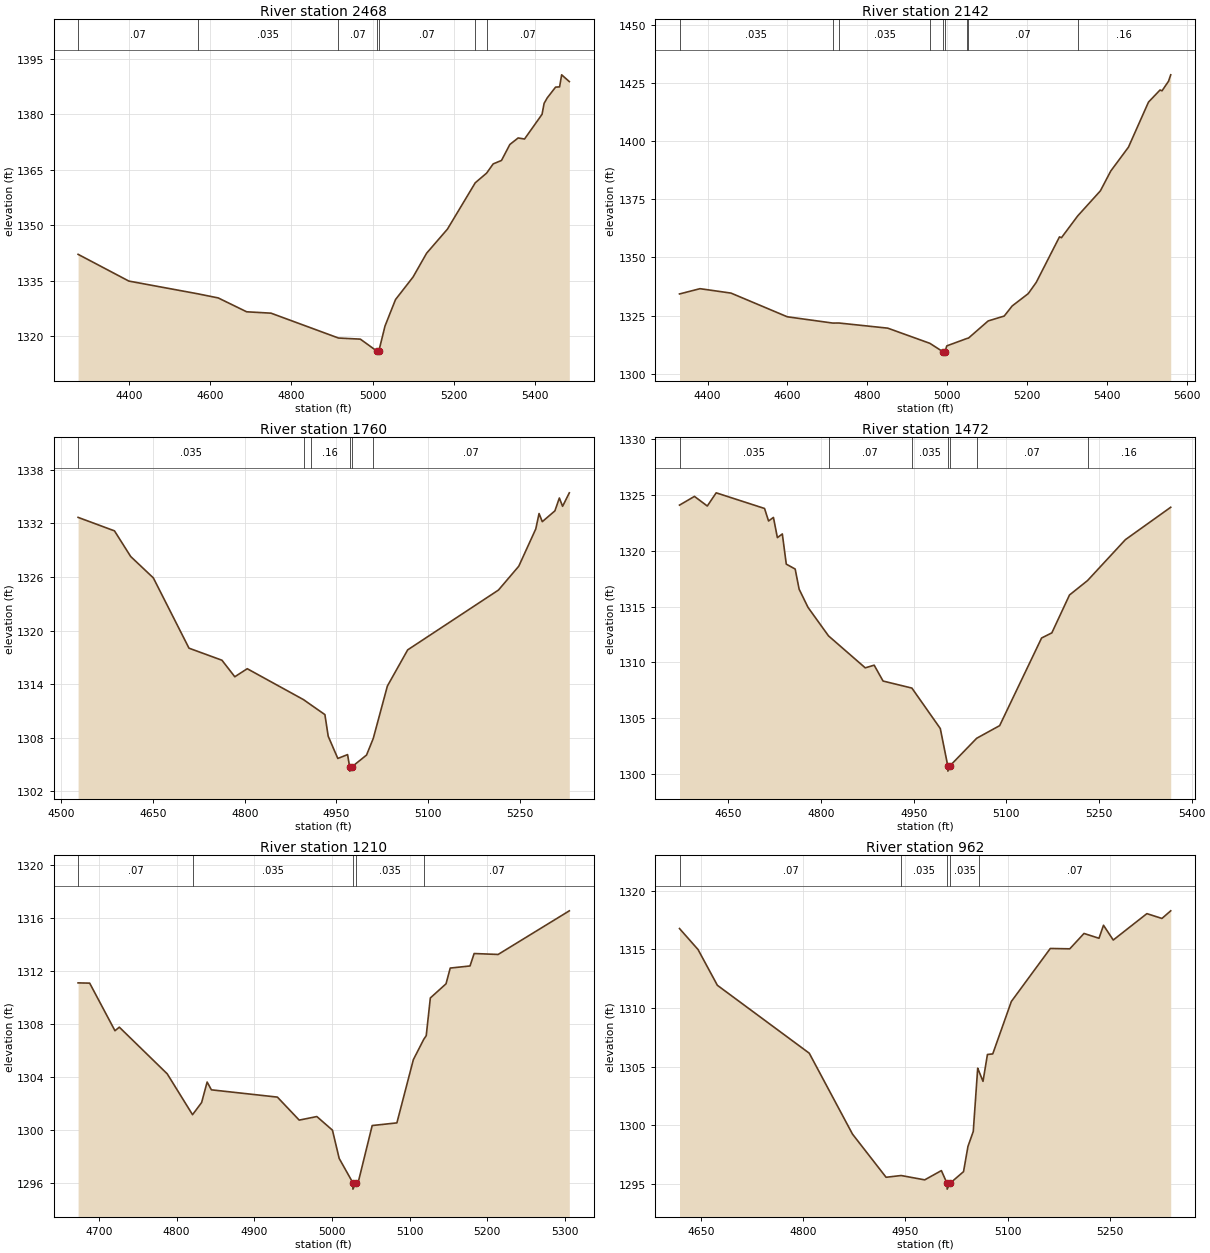
Type RM Length L Ch R = 1,2468,326,326,326
BEGIN DESCRIPTION:
Chimney Creek 1200 5.0
END DESCRIPTION:
XS GIS Cut Line= 3
      1697480.00      7062862.99      1697452.52      7062138.01
      1697345.76      7061665.01
#Sta/Elev= 30
  4274.5 1342.20  4399.6 1334.97  4569.0 1331.54  4619.7 1330.42  4689.8 1326.67
  4749.8 1326.30  4916.1 1319.58  4970.0 1319.28  5011.4 1316.00  5011.7 1315.50
  5015.4 1316.00  5030.8 1322.84  5056.6 1329.97  5099.8 1336.06  5133.3 1342.51
  5184.5 1349.00  5253.1 1361.53  5281.2 1364.16  5297.3 1366.64  5317.8 1367.57
  5338.3 1371.88  5358.8 1373.65  5374.5 1373.36  5417.7 1380.04  5422.8 1383.01
  5430.6 1384.50  5451.1 1387.39  5460.9 1387.45  5466.0 1390.71  5484.9 1388.88
#Mann=7,-1,0
  4274.5    0.07       0  4569.0   0.035       0  4916.1    0.07       0
  5011.4    0.07       0  5015.4    0.07       0  5253.1    0.16       0
  5281.2    0.07       0
Bank Sta=5011.4,5015.4
Exp/Cntr=0.3,0.1

Type RM Length L Ch R = 1,2142,382,382,382
BEGIN DESCRIPTION:
Mapping XS 8effa3e6
END DESCRIPTION:
XS GIS Cut Line= 3
      1697835.34      7062756.14      1697762.42      7062089.46
      1697718.18      7061532.57
#Sta/Elev= 30
  4329.8 1334.27  4381.1 1336.54  4458.7 1334.64  4599.5 1324.45  4713.3 1321.75
  4729.0 1321.77  4851.0 1319.56  4956.3 1313.04  4989.9 1309.32  4990.1 1308.82
  4993.9 1309.32  4998.7 1311.94  5049.7 1315.16  5053.0 1315.29  5102.2 1322.66
  5142.4 1324.77  5162.4 1329.12  5202.5 1334.41  5222.6 1339.27  5280.7 1358.82
  5285.7 1358.48  5326.3 1367.84  5383.1 1378.63  5409.0 1387.14  5453.3 1397.41
  5503.5 1416.81  5532.3 1421.99  5537.4 1421.67  5553.6 1425.78  5559.1 1428.53
#Mann=9,-1,0
  4329.8   0.035       0  4713.3    0.07       0  4729.0   0.035       0
  4956.3    0.07       0  4989.9    0.07       0  4993.9    0.07       0
  5049.7    0.16       0  5053.0    0.07       0  5326.3    0.16       0
Bank Sta=4989.9,4993.9
Exp/Cntr=0.3,0.1

Type RM Length L Ch R = 1,1760,288,288,288
BEGIN DESCRIPTION:
Mapping XS e433cc14
END DESCRIPTION:
XS GIS Cut Line= 3
      1697972.03      7062601.48      1698119.61      7062153.33
      1698214.02      7061835.37
#Sta/Elev= 30
  4527.5 1332.68  4587.0 1331.17  4613.5 1328.30  4650.6 1325.90  4708.9 1318.03
  4762.8 1316.68  4783.8 1314.83  4804.2 1315.73  4896.4 1312.26  4908.2 1311.69
  4931.2 1310.59  4936.6 1308.17  4952.3 1305.68  4968.3 1306.11  4971.6 1304.76
  4971.9 1304.26  4975.7 1304.76  4999.3 1306.06  5010.3 1307.92  5033.4 1313.79
  5066.6 1317.84  5215.1 1324.54  5248.3 1327.21  5276.1 1331.38  5281.5 1333.11
  5286.8 1332.20  5307.4 1333.41  5314.7 1334.85  5320.0 1333.92  5331.0 1335.43
#Mann=6,-1,0
  4527.5   0.035       0  4896.4    0.07       0  4908.2    0.16       0
  4971.6    0.07       0  4975.7    0.16       0  5010.3    0.07       0
Bank Sta=4971.6,4975.7
Exp/Cntr=0.3,0.1

Type RM Length L Ch R = 1,1472,262,262,262
BEGIN DESCRIPTION:
Mapping XS 557b9f2e
END DESCRIPTION:
XS GIS Cut Line= 3
      1698071.83      7062658.14      1698342.05      7062323.90
      1698500.78      7061994.56
#Sta/Elev= 30
  4570.7 1324.08  4594.9 1324.86  4615.7 1324.00  4630.1 1325.18  4708.4 1323.78
  4714.9 1322.66  4722.8 1322.98  4729.2 1321.17  4737.2 1321.50  4743.6 1318.80
  4758.0 1318.36  4764.4 1316.56  4778.8 1314.93  4812.0 1312.38  4871.5 1309.52
  4885.9 1309.76  4900.3 1308.34  4947.0 1307.71  4993.0 1304.09  5005.0 1300.78
  5005.3 1300.28  5009.1 1300.78  5051.9 1303.22  5089.1 1304.35  5157.0 1312.19
  5173.6 1312.65  5202.2 1316.04  5231.4 1317.33  5292.7 1320.99  5366.1 1323.89
#Mann=7,-1,0
  4570.7   0.035       0  4812.0    0.07       0  4947.0   0.035       0
  5005.0   0.035       0  5009.1   0.035       0  5051.9    0.07       0
  5231.4    0.16       0
Bank Sta=5005,5009.1
Exp/Cntr=0.3,0.1

Type RM Length L Ch R = 1,1210,248,248,248
BEGIN DESCRIPTION:
Mapping XS 8e5d8cd6
END DESCRIPTION:
XS GIS Cut Line= 3
      1698427.26      7062731.39      1698569.41      7062436.25
      1698671.41      7062148.69
#Sta/Elev= 30
  4673.1 1311.11  4688.0 1311.09  4720.6 1307.49  4726.2 1307.76  4787.9 1304.23
  4820.5 1301.14  4832.2 1302.06  4839.3 1303.61  4844.8 1303.02  4929.8 1302.47
  4957.9 1300.73  4980.6 1301.00  5000.7 1299.97  5009.4 1297.83  5026.8 1296.01
  5027.1 1295.51  5030.9 1296.01  5034.2 1296.10  5051.9 1300.32  5083.7 1300.52
  5104.9 1305.30  5118.3 1306.84  5121.5 1307.12  5126.8 1309.97  5147.0 1311.04
  5152.4 1312.23  5177.9 1312.39  5183.2 1313.33  5214.1 1313.26  5305.8 1316.56
#Mann=5,-1,0
  4673.1    0.07       0  4820.5   0.035       0  5026.8   0.035       0
  5030.9   0.035       0  5118.3    0.07       0
Bank Sta=5026.8,5030.9
Exp/Cntr=0.3,0.1

Type RM Length L Ch R = 1,962,190,190,190
BEGIN DESCRIPTION:
Mapping XS 0043b483
END DESCRIPTION:
XS GIS Cut Line= 3
      1698495.64      7062847.47      1698754.95      7062568.62
      1698974.16      7062308.18
#Sta/Elev= 30
  4618.3 1316.77  4645.5 1314.98  4673.9 1311.93  4808.8 1306.14  4872.3 1299.24
  4921.6 1295.56  4943.7 1295.71  4978.3 1295.34  5002.8 1296.13  5011.0 1295.05
  5011.3 1294.55  5015.5 1295.05  5035.3 1296.04  5041.8 1298.19  5049.6 1299.47
  5056.1 1304.86  5057.8 1304.62  5063.9 1303.74  5070.4 1306.03  5078.2 1306.08
  5105.5 1310.55  5162.7 1315.07  5191.3 1315.04  5212.2 1316.35  5234.2 1315.94
  5240.8 1317.05  5255.1 1315.79  5304.5 1318.04  5326.6 1317.63  5339.5 1318.28
#Mann=5,-1,0
  4618.3    0.07       0  4943.7   0.035       0  5011.0   0.035       0
  5015.5   0.035       0  5057.8    0.07       0
Bank Sta=5011,5015.5
Exp/Cntr=0.3,0.1

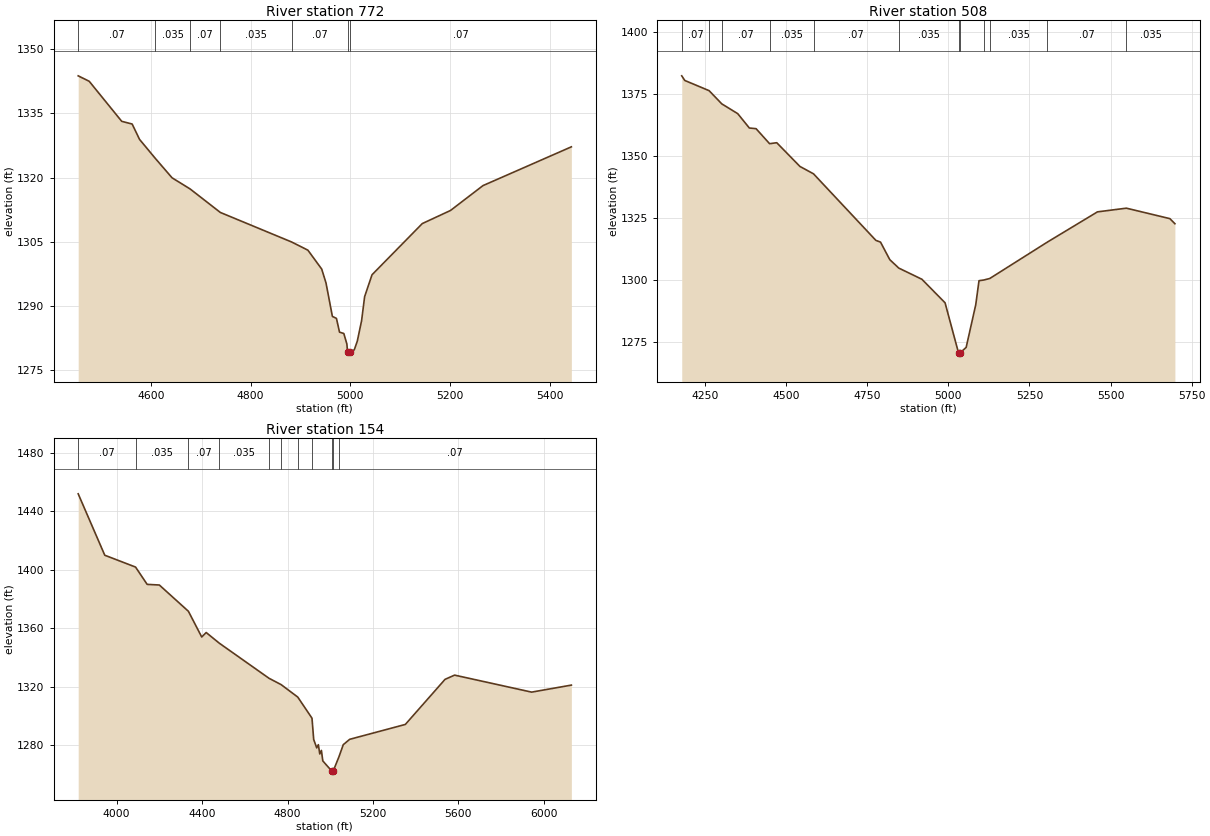
Type RM Length L Ch R = 1,772,264,264,264
BEGIN DESCRIPTION:
Mapping XS d3fbddb6
END DESCRIPTION:
XS GIS Cut Line= 3
      1698528.27      7063172.56      1698844.23      7062729.86
      1699102.92      7062368.74
#Sta/Elev= 30
  4454.7 1343.78  4476.8 1342.50  4541.9 1333.15  4562.8 1332.52  4577.6 1328.93
  4608.5 1324.59  4642.7 1319.96  4678.8 1317.36  4739.5 1311.86  4882.1 1304.97
  4914.9 1303.05  4942.6 1298.63  4951.2 1295.39  4964.0 1287.57  4972.1 1287.11
  4978.3 1283.89  4986.9 1283.58  4993.0 1281.14  4994.4 1279.26  4994.7 1278.76
  4999.0 1279.26  5007.8 1279.75  5013.9 1281.79  5022.5 1286.57  5028.6 1292.19
  5043.4 1297.30  5144.1 1309.26  5200.6 1312.32  5265.7 1318.13  5442.8 1327.19
#Mann=7,-1,0
  4454.7    0.07       0  4608.5   0.035       0  4678.8    0.07       0
  4739.5   0.035       0  4882.1    0.07       0  4994.4    0.07       0
  4999.0    0.07       0
Bank Sta=4994.4,4999
Exp/Cntr=0.3,0.1

Type RM Length L Ch R = 1,508,354,354,354
BEGIN DESCRIPTION:
Mapping XS a3353d06
END DESCRIPTION:
XS GIS Cut Line= 3
      1698523.66      7063509.85      1699050.83      7062886.11
      1699166.80      7062192.62
#Sta/Elev= 30
  4178.6 1382.28  4188.0 1380.41  4262.9 1376.31  4302.0 1370.99  4351.2 1367.04
  4386.9 1361.27  4407.7 1360.99  4449.3 1354.95  4471.4 1355.34  4542.9 1345.78
  4584.7 1342.81  4776.9 1316.01  4791.2 1315.31  4819.8 1308.24  4847.5 1304.85
  4918.7 1300.35  4990.1 1290.87  5031.6 1270.70  5032.0 1270.20  5036.2 1270.70
  5055.1 1272.91  5084.6 1290.06  5094.7 1299.77  5109.9 1300.06  5128.0 1300.67
  5305.0 1315.29  5459.7 1327.49  5548.8 1328.98  5682.8 1324.77  5698.4 1322.72
#Mann=12,-1,0
  4178.6    0.07       0  4262.9   0.035       0  4302.0    0.07       0
  4449.3   0.035       0  4584.7    0.07       0  4847.5   0.035       0
  5031.6   0.035       0  5036.2   0.035       0  5109.9    0.07       0
  5128.0   0.035       0  5305.0    0.07       0  5548.8   0.035       0
Bank Sta=5031.6,5036.2
Exp/Cntr=0.3,0.1

Type RM Length L Ch R = 1,154,0,0,0
BEGIN DESCRIPTION:
Chimney Creek 1200 1.0
END DESCRIPTION:
XS GIS Cut Line= 3
      1698474.18      7063772.88      1699364.67      7062998.81
      1699291.92      7061872.45
#Sta/Elev= 30
  3820.1 1451.97  3944.5 1410.01  4088.6 1401.92  4142.9 1390.09  4199.9 1389.66
  4336.0 1371.71  4398.4 1354.12  4419.2 1357.19  4480.6 1349.91  4713.4 1325.92
  4770.0 1321.59  4847.9 1313.08  4914.6 1298.63  4922.5 1284.08  4936.7 1278.34
  4944.3 1280.55  4951.0 1274.19  4958.6 1276.61  4965.2 1269.45  5008.5 1262.29
  5008.8 1261.79  5013.1 1262.29  5040.3 1272.10  5060.9 1280.54  5091.0 1284.21
  5351.5 1294.38  5537.4 1325.19  5582.0 1328.08  5942.8 1316.46  6128.7 1321.26
#Mann=11,-1,0
  3820.1    0.07       0  4088.6   0.035       0  4336.0    0.07       0
  4480.6   0.035       0  4713.4    0.07       0  4770.0   0.035       0
  4847.9    0.07       0  4914.6   0.035       0  5008.5   0.035       0
  5013.1   0.035       0  5040.3    0.07       0
Bank Sta=5008.5,5013.1
Exp/Cntr=0.3,0.1

Chan Stop Cuts=-1