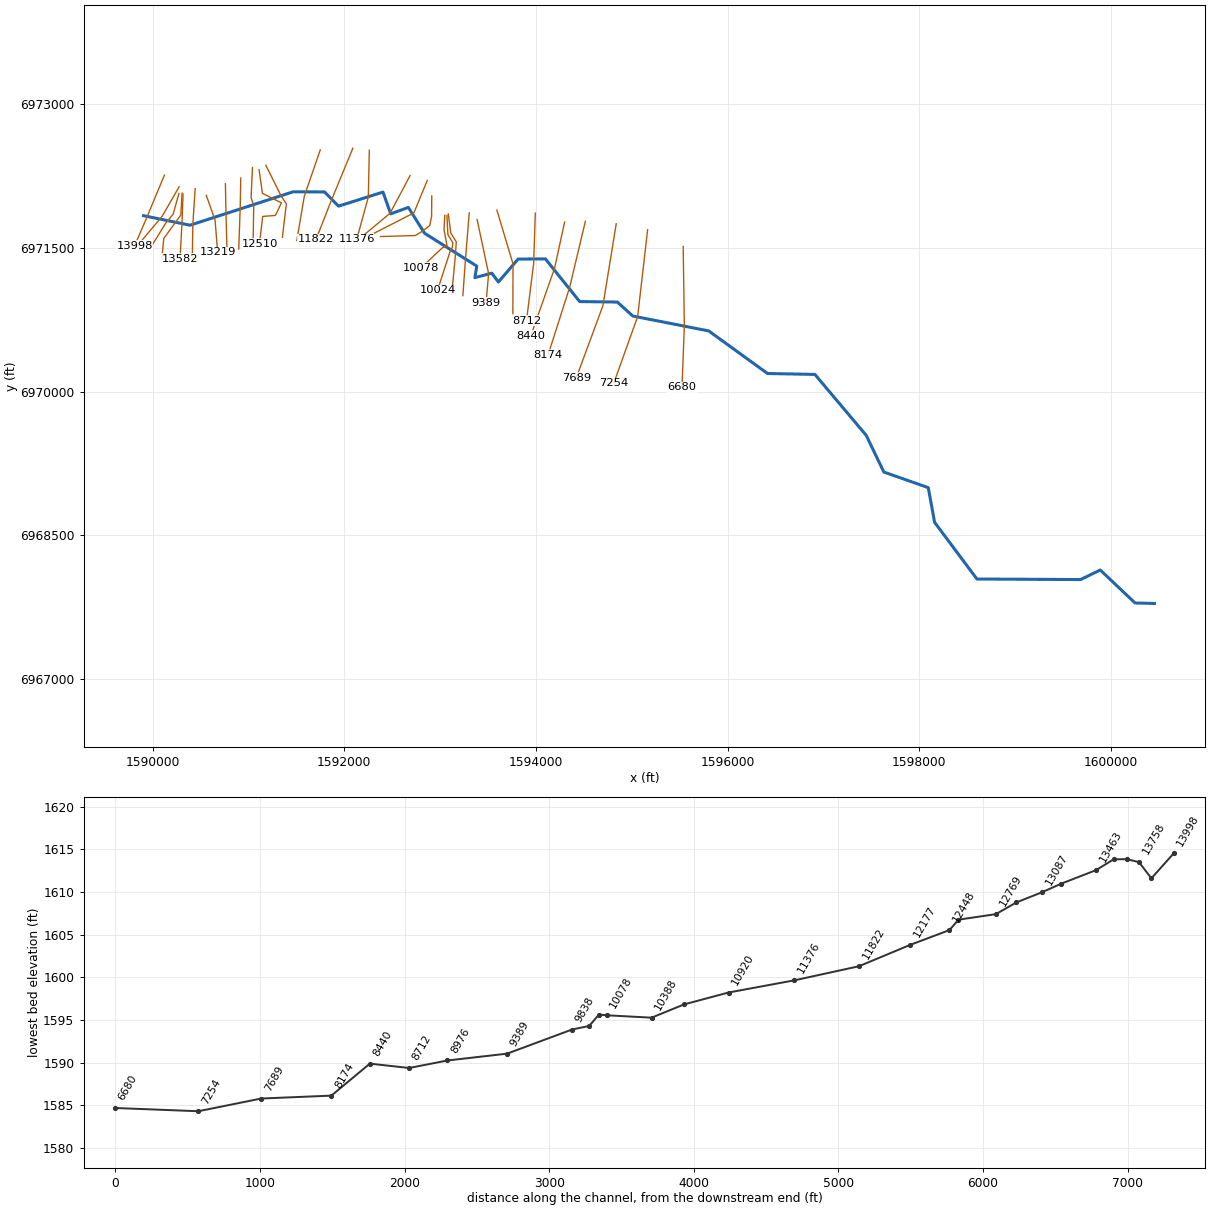
--- Chimney Creek 1201.prj (project) ---

Proj Title=Chimney Creek 1201 Base Level Engineering
Current Plan=p01
Default Exp/Contr=0.3,0.1
English Units
Geom File=g01
Flow File=f01
Plan File=p01
BEGIN DESCRIPTION:
Chimney Creek 1201
END DESCRIPTION:

--- Chimney Creek 1201.p01 (plan) ---

Plan Title=Multiple Run
Short Identifier=Multiple
Geom File=g01
Flow File=f01
Subcritical Flow
K Sum by GR= 0
Std Step Tol= 0.01
Critical Tol= 0.01
Num of Std Step Trials= 20
Max Error Tol= 0.3
Flow Tol Ratio= 0.001
Split Flow NTrial= 30
Split Flow Tol= 0.02
Split Flow Ratio= 0.02
Log Output Level= 0
Friction Slope Method= 1
Unsteady Friction Slope Method= 2
Unsteady Bridges Friction Slope Method= 1
Parabolic Critical Depth
Global Vel Dist=  1 , 1 , 1
Global Log Level= 0
CheckData=True
Encroach Param= -1, 0, 0, 0
BEGIN DESCRIPTION:
Multiple Run
END DESCRIPTION:

--- Chimney Creek 1201.f01 (steady flow) ---

Flow Title=Multiple
Number of Profiles=7
Profile Names=10-year,25-year,50-year,1pct_min,100-year,1pct_plu,500-year
River Rch & RM= Chimney Creek 12,Reach-1,13998
     196     265     320     192     384     765     560
River Rch & RM= Chimney Creek 12,Reach-1,12769
     306     424     520     317     633    1264     952
River Rch & RM= Chimney Creek 12,Reach-1,343
     438     618     769     475     948    1892    1461
Boundary for River Rch & Prof#=Chimney Creek 12,Reach-1,1
Up Type=0
Dn Type=3
Dn Slope=0.005
Boundary for River Rch & Prof#=Chimney Creek 12,Reach-1,2
Up Type=0
Dn Type=3
Dn Slope=0.005
Boundary for River Rch & Prof#=Chimney Creek 12,Reach-1,3
Up Type=0
Dn Type=3
Dn Slope=0.005
Boundary for River Rch & Prof#=Chimney Creek 12,Reach-1,4
Up Type=0
Dn Type=3
Dn Slope=0.005
Boundary for River Rch & Prof#=Chimney Creek 12,Reach-1,5
Up Type=0
Dn Type=3
Dn Slope=0.005
Boundary for River Rch & Prof#=Chimney Creek 12,Reach-1,6
Up Type=0
Dn Type=3
Dn Slope=0.005
Boundary for River Rch & Prof#=Chimney Creek 12,Reach-1,7
Up Type=0
Dn Type=3
Dn Slope=0.005

--- Chimney Creek 1201.g01 (geometry) ---

Geom Title=Existing Conditions

River Reach=Chimney Creek 12,Reach-1
Reach XY= 30
      1589905.00      6971838.00      1590389.78      6971738.52
      1591464.85      6972087.07      1591793.17      6972086.39
      1591939.79      6971937.51      1592403.53      6972084.54
      1592484.38      6971857.12      1592668.38      6971924.48
      1592837.87      6971654.45      1593382.56      6971311.40
      1593362.60      6971190.98      1593538.99      6971237.74
      1593608.17      6971145.53      1593813.62      6971385.04
      1594098.97      6971386.38      1594456.42      6970941.04
      1594849.11      6970936.03      1595010.85      6970790.06
      1595803.53      6970634.45      1596416.99      6970189.80
      1596911.46      6970180.26      1597446.87      6969544.07
      1597631.10      6969160.71      1598094.53      6968997.83
      1598160.83      6968635.70      1598602.55      6968043.45
      1599685.02      6968037.96      1599889.78      6968137.76
      1600252.57      6967793.40      1600455.00      6967788.00

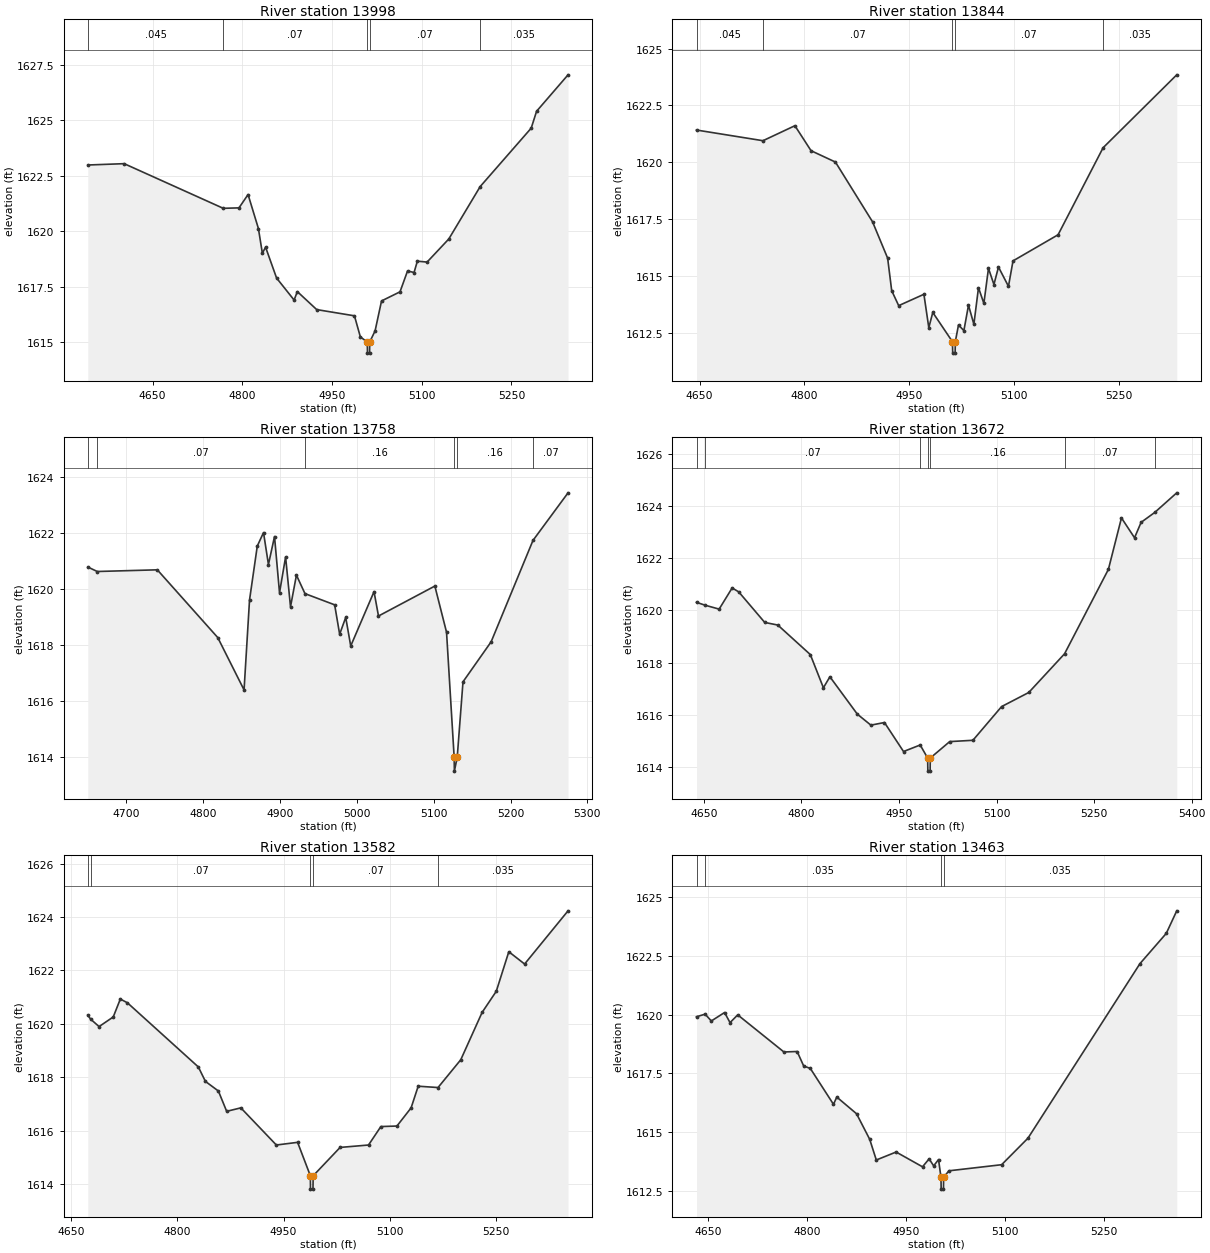
Type RM Length L Ch R = 1,13998,154,154,154
BEGIN DESCRIPTION:
Chimney Creek 1201 20.0
END DESCRIPTION:
XS GIS Cut Line= 3
      1590122.34      6972261.51      1589946.56      6971838.05
      1589810.71      6971521.35
#Sta/Elev= 30
  4541.5 1622.99  4602.3 1623.05  4768.0 1621.04  4794.3 1621.06  4809.5 1621.66
  4826.8 1620.13  4833.4 1619.02  4838.8 1619.29  4857.2 1617.90  4886.5 1616.91
  4891.9 1617.29  4924.3 1616.48  4987.4 1616.20  4997.3 1615.25  5008.9 1615.02
  5009.2 1614.52  5012.7 1614.52  5012.9 1615.02  5021.9 1615.52  5032.7 1616.87
  5063.6 1617.28  5076.2 1618.22  5087.1 1618.15  5092.6 1618.66  5108.9 1618.62
  5145.2 1619.66  5197.7 1622.02  5283.0 1624.65  5292.0 1625.41  5344.6 1627.05
#Mann=5,-1,0
  4541.5   0.045       0  4768.0    0.07       0  5008.9    0.07       0
  5012.9    0.07       0  5197.7   0.035       0
Bank Sta=5008.9,5012.9
Exp/Cntr=0.3,0.1

Type RM Length L Ch R = 1,13844,86,86,86
BEGIN DESCRIPTION:
Mapping XS 55c33210
END DESCRIPTION:
XS GIS Cut Line= 3
      1590276.43      6972140.01      1590099.55      6971832.79
      1589885.76      6971577.88
#Sta/Elev= 30
  4645.5 1621.42  4740.6 1620.95  4786.3 1621.61  4809.4 1620.51  4844.3 1620.01
  4897.4 1617.38  4919.0 1615.78  4924.8 1614.35  4934.8 1613.69  4970.9 1614.19
  4977.9 1612.72  4983.6 1613.39  5011.8 1612.10  5012.1 1611.60  5015.6 1611.60
  5015.8 1612.10  5020.4 1612.84  5028.1 1612.59  5034.7 1613.71  5042.4 1612.87
  5049.0 1614.48  5056.7 1613.79  5063.3 1615.33  5071.1 1614.62  5077.6 1615.39
  5091.9 1614.54  5098.4 1615.66  5162.9 1616.81  5227.3 1620.64  5332.7 1623.85
#Mann=5,-1,0
  4645.5   0.045       0  4740.6    0.07       0  5011.8    0.07       0
  5015.8    0.07       0  5227.3   0.035       0
Bank Sta=5011.8,5015.8
Exp/Cntr=0.3,0.1

Type RM Length L Ch R = 1,13758,86,86,86
BEGIN DESCRIPTION:
Mapping XS 1112b689
END DESCRIPTION:
XS GIS Cut Line= 4
      1590274.25      6972070.54      1590213.48      6971853.53
      1590135.36      6971758.04      1589989.98      6971523.71
#Sta/Elev= 30
  4650.3 1620.79  4662.6 1620.63  4740.7 1620.69  4819.3 1618.27  4853.5 1616.40
  4860.6 1619.61  4870.7 1621.54  4878.8 1622.02  4885.2 1620.88  4893.1 1621.88
  4899.6 1619.87  4907.5 1621.15  4913.9 1619.37  4921.6 1620.50  4932.7 1619.84
  4971.3 1619.44  4977.8 1618.39  4985.7 1618.99  4992.2 1617.97  5022.5 1619.91
  5028.3 1619.04  5101.6 1620.11  5116.8 1618.46  5126.7 1614.00  5127.0 1613.50
  5130.7 1614.00  5138.2 1616.69  5174.8 1618.12  5229.2 1621.74  5274.8 1623.44
#Mann=6,-1,0
  4650.3   0.045       0  4662.6    0.07       0  4932.7    0.16       0
  5126.7    0.07       0  5130.7    0.16       0  5229.2    0.07       0
Bank Sta=5126.7,5130.7
Exp/Cntr=0.3,0.1

Type RM Length L Ch R = 1,13672,90,90,90
BEGIN DESCRIPTION:
Mapping XS cf0051f3
END DESCRIPTION:
XS GIS Cut Line= 5
      1590306.80      6972072.75      1590293.78      6971844.84
      1590215.65      6971738.51      1590115.82      6971599.62
      1590096.29      6971393.41
#Sta/Elev= 30
  4638.7 1620.31  4651.8 1620.20  4673.5 1620.05  4693.5 1620.86  4703.6 1620.71
  4743.6 1619.54  4763.7 1619.44  4813.7 1618.31  4833.8 1617.04  4843.8 1617.46
  4886.0 1616.03  4906.8 1615.61  4927.7 1615.71  4957.0 1614.60  4982.6 1614.85
  4994.1 1614.35  4994.4 1613.85  4997.9 1613.85  4998.1 1614.35  5028.0 1614.98
  5063.7 1615.03  5107.8 1616.32  5149.6 1616.86  5204.6 1618.34  5272.0 1621.57
  5292.1 1623.54  5312.2 1622.78  5322.3 1623.37  5343.3 1623.75  5377.1 1624.50
#Mann=7,-1,0
  4638.7   0.045       0  4651.8    0.07       0  4982.6    0.16       0
  4994.1    0.07       0  4998.1    0.16       0  5204.6    0.07       0
  5343.3   0.045       0
Bank Sta=4994.1,4998.1
Exp/Cntr=0.3,0.1

Type RM Length L Ch R = 1,13582,119,119,119
BEGIN DESCRIPTION:
Mapping XS 2372b2f7
END DESCRIPTION:
XS GIS Cut Line= 3
      1590316.78      6972063.88      1590305.06      6971739.70
      1590285.53      6971386.84
#Sta/Elev= 30
  4673.8 1620.33  4677.7 1620.18  4689.7 1619.90  4709.7 1620.26  4719.7 1620.93
  4729.7 1620.79  4829.8 1618.39  4839.8 1617.85  4858.1 1617.49  4869.8 1616.73
  4889.8 1616.86  4939.9 1615.47  4969.9 1615.57  4987.9 1614.32  4988.1 1613.82
  4991.6 1613.82  4991.9 1614.32  5029.9 1615.38  5070.0 1615.47  5087.4 1616.16
  5110.1 1616.18  5130.1 1616.86  5140.1 1617.67  5168.1 1617.62  5200.2 1618.66
  5230.3 1620.43  5250.3 1621.22  5268.0 1622.70  5290.3 1622.24  5351.6 1624.23
#Mann=5,-1,0
  4673.8   0.045       0  4677.7    0.07       0  4987.9    0.07       0
  4991.9    0.07       0  5168.1   0.035       0
Bank Sta=4987.9,4991.9
Exp/Cntr=0.3,0.1

Type RM Length L Ch R = 1,13463,244,244,244
BEGIN DESCRIPTION:
Mapping XS bcca2d81
END DESCRIPTION:
XS GIS Cut Line= 3
      1590443.52      6972120.46      1590419.64      6971753.70
      1590413.15      6971392.10
#Sta/Elev= 30
  4631.9 1619.91  4645.0 1620.02  4654.4 1619.73  4674.5 1620.09  4682.8 1619.66
  4694.5 1619.99  4764.6 1618.41  4784.7 1618.43  4794.7 1617.81  4804.7 1617.71
  4839.9 1616.18  4844.9 1616.49  4874.9 1615.78  4894.9 1614.69  4904.9 1613.81
  4935.0 1614.15  4975.1 1613.52  4985.1 1613.86  4992.0 1613.56  4999.4 1613.83
  5003.1 1613.07  5003.4 1612.57  5006.9 1612.57  5007.1 1613.07  5015.1 1613.35
  5095.2 1613.61  5135.2 1614.74  5305.2 1622.17  5345.2 1623.46  5361.1 1624.42
#Mann=4,-1,0
  4631.9    0.07       0  4645.0   0.035       0  5003.1   0.035       0
  5007.1   0.035       0
Bank Sta=5003.1,5007.1
Exp/Cntr=0.3,0.1

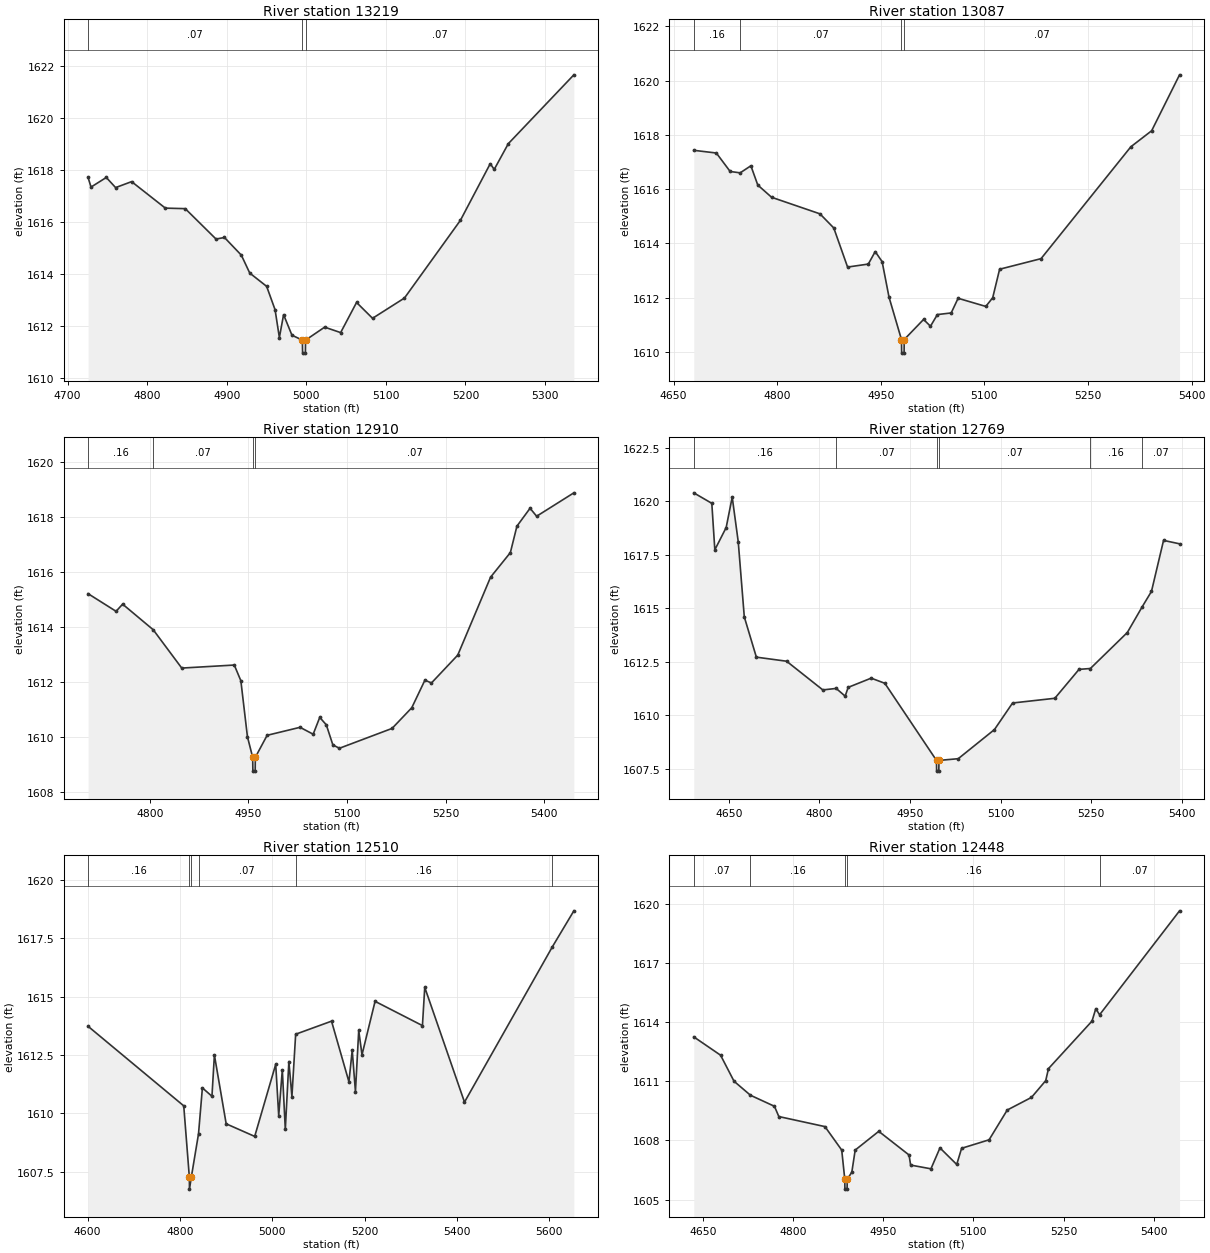
Type RM Length L Ch R = 1,13219,132,132,132
BEGIN DESCRIPTION:
Mapping XS af476e2e
END DESCRIPTION:
XS GIS Cut Line= 3
      1590559.84      6972049.58      1590650.98      6971791.78
      1590678.33      6971455.83
#Sta/Elev= 30
  4725.7 1617.72  4729.4 1617.35  4748.6 1617.72  4760.3 1617.33  4780.4 1617.56
  4822.8 1616.54  4847.8 1616.52  4886.5 1615.35  4897.1 1615.41  4918.3 1614.73
  4928.9 1614.04  4950.1 1613.53  4960.7 1612.63  4966.1 1611.56  4971.4 1612.44
  4981.9 1611.65  4995.0 1611.46  4995.3 1610.96  4998.8 1610.96  4999.0 1611.46
  5023.0 1611.96  5043.1 1611.75  5063.1 1612.91  5083.2 1612.30  5123.3 1613.08
  5193.6 1616.07  5231.1 1618.25  5236.1 1618.03  5253.8 1619.02  5336.2 1621.67
#Mann=3,-1,0
  4725.7    0.07       0  4995.0    0.07       0  4999.0    0.07       0
Bank Sta=4995,4999
Exp/Cntr=0.3,0.1

Type RM Length L Ch R = 1,13087,177,177,177
BEGIN DESCRIPTION:
Mapping XS 09fb6d63
END DESCRIPTION:
XS GIS Cut Line= 3
      1590759.05      6972170.66      1590765.56      6971850.38
      1590775.98      6971467.57
#Sta/Elev= 30
  4679.2 1617.43  4711.9 1617.33  4731.9 1616.65  4746.4 1616.60  4761.9 1616.86
  4771.9 1616.15  4791.9 1615.70  4861.9 1615.09  4881.9 1614.57  4901.9 1613.13
  4931.9 1613.24  4941.9 1613.70  4951.9 1613.33  4961.9 1612.02  4979.9 1610.46
  4980.2 1609.96  4983.7 1609.96  4983.9 1610.46  5011.9 1611.20  5021.9 1610.95
  5031.9 1611.38  5051.9 1611.44  5061.9 1611.98  5102.0 1611.68  5112.0 1612.00
  5122.0 1613.05  5182.0 1613.44  5312.0 1617.56  5342.1 1618.15  5382.5 1620.21
#Mann=4,-1,0
  4679.2    0.16       0  4746.4    0.07       0  4979.9    0.07       0
  4983.9    0.07       0
Bank Sta=4979.9,4983.9
Exp/Cntr=0.3,0.1

Type RM Length L Ch R = 1,12910,141,141,141
BEGIN DESCRIPTION:
Mapping XS 77ace52d
END DESCRIPTION:
XS GIS Cut Line= 3
      1590919.21      6972230.60      1590914.00      6971937.62
      1590898.43      6971491.32
#Sta/Elev= 30
  4705.8 1615.21  4748.4 1614.57  4758.4 1614.83  4805.0 1613.90  4848.4 1612.51
  4928.4 1612.62  4938.4 1612.05  4948.4 1610.02  4956.4 1609.27  4956.7 1608.77
  4960.2 1608.77  4960.4 1609.27  4978.4 1610.07  5028.5 1610.36  5048.5 1610.11
  5058.5 1610.72  5068.5 1610.45  5078.5 1609.72  5088.5 1609.60  5168.6 1610.32
  5198.6 1611.07  5218.6 1612.07  5228.6 1611.97  5268.6 1612.98  5318.6 1615.81
  5348.7 1616.70  5358.7 1617.66  5378.7 1618.31  5388.7 1618.02  5445.4 1618.87
#Mann=4,-1,0
  4705.8    0.16       0  4805.0    0.07       0  4956.4    0.07       0
  4960.4    0.07       0
Bank Sta=4956.4,4960.4
Exp/Cntr=0.3,0.1

Type RM Length L Ch R = 1,12769,259,259,259
BEGIN DESCRIPTION:
Mapping XS d887030a
END DESCRIPTION:
XS GIS Cut Line= 4
      1591041.41      6972341.62      1591027.24      6972028.16
      1591054.58      6971940.92      1591048.10      6971541.47
#Sta/Elev= 30
  4591.8 1620.39  4621.7 1619.90  4626.7 1617.73  4645.5 1618.77  4655.5 1620.19
  4665.5 1618.10  4675.5 1614.60  4695.5 1612.72  4745.6 1612.53  4805.6 1611.19
  4827.7 1611.26  4842.6 1610.90  4847.6 1611.31  4885.7 1611.74  4908.3 1611.50
  4993.9 1607.90  4994.1 1607.40  4997.7 1607.40  4998.0 1607.90  5029.9 1607.98
  5089.9 1609.34  5119.9 1610.58  5189.9 1610.80  5230.0 1612.15  5248.8 1612.19
  5310.0 1613.87  5334.2 1615.05  5350.0 1615.79  5370.0 1618.17  5396.5 1618.01
#Mann=6,-1,0
  4591.8    0.16       0  4827.7    0.07       0  4993.9    0.07       0
  4998.0    0.07       0  5248.8    0.16       0  5334.2    0.07       0
Bank Sta=4993.9,4998
Exp/Cntr=0.3,0.1

Type RM Length L Ch R = 1,12510,62,62,62
BEGIN DESCRIPTION:
Mapping XS 710aebb9
END DESCRIPTION:
XS GIS Cut Line= 6
      1591110.58      6972317.20      1591145.73      6972071.13
      1591343.65      6971972.17      1591281.15      6971840.66
      1591148.33      6971830.24      1591114.51      6971542.72
#Sta/Elev= 30
  4600.9 1613.73  4808.1 1610.32  4820.3 1607.25  4820.5 1606.75  4824.4 1607.25
  4840.1 1609.12  4848.5 1611.09  4869.2 1610.73  4874.5 1612.50  4900.0 1609.55
  4961.8 1609.01  5007.3 1612.10  5013.8 1609.90  5021.6 1611.86  5028.1 1609.31
  5035.8 1612.22  5042.4 1610.72  5050.5 1613.39  5128.2 1613.95  5165.9 1611.35
  5173.0 1612.70  5180.0 1610.93  5187.1 1613.55  5194.2 1612.51  5222.5 1614.80
  5325.1 1613.76  5330.1 1615.40  5416.2 1610.48  5606.6 1617.14  5653.1 1618.68
#Mann=6,-1,0
  4600.9    0.16       0  4820.3    0.07       0  4824.4    0.16       0
  4840.1    0.07       0  5050.5    0.16       0  5606.6    0.07       0
Bank Sta=4820.3,4824.4
Exp/Cntr=0.3,0.1

Type RM Length L Ch R = 1,12448,271,271,271
BEGIN DESCRIPTION:
Mapping XS e17aea2e
END DESCRIPTION:
XS GIS Cut Line= 5
      1591180.95      6972364.66      1591342.39      6972040.48
      1591395.77      6971961.06      1591378.85      6971826.94
      1591354.11      6971613.40
#Sta/Elev= 30
  4635.0 1613.25  4679.6 1612.32  4702.0 1611.00  4729.3 1610.29  4769.2 1609.73
  4776.5 1609.21  4853.2 1608.70  4881.1 1607.51  4886.2 1606.03  4886.4 1605.53
  4890.0 1605.53  4890.3 1606.03  4897.9 1606.39  4903.5 1607.51  4942.7 1608.46
  4993.1 1607.26  4995.7 1606.75  5029.5 1606.56  5044.5 1607.62  5072.4 1606.78
  5080.5 1607.60  5126.2 1608.03  5156.4 1609.54  5196.7 1610.18  5220.4 1611.03
  5225.0 1611.64  5297.4 1614.05  5303.7 1614.68  5310.0 1614.37  5443.0 1619.64
#Mann=5,-1,0
  4635.0    0.07       0  4729.3    0.16       0  4886.2    0.07       0
  4890.3    0.16       0  5310.0    0.07       0
Bank Sta=4886.2,4890.3
Exp/Cntr=0.3,0.1

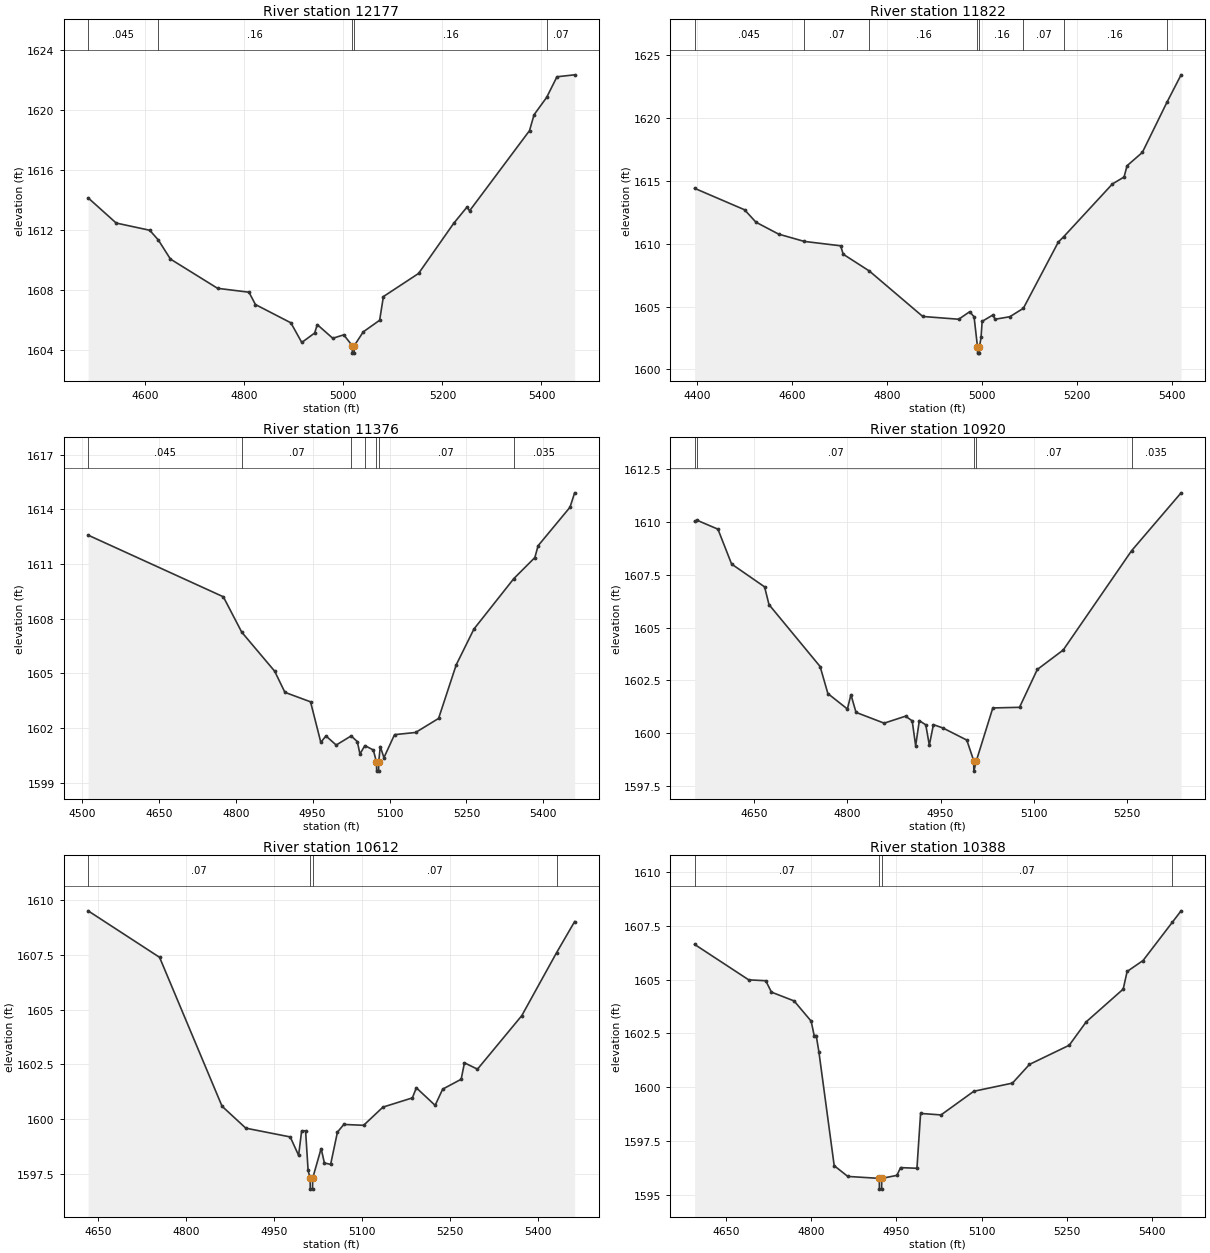
Type RM Length L Ch R = 1,12177,355,355,355
BEGIN DESCRIPTION:
Mapping XS 6542442c
END DESCRIPTION:
XS GIS Cut Line= 3
      1591748.95      6972525.13      1591582.27      6972040.74
      1591504.16      6971577.24
#Sta/Elev= 30
  4484.6 1614.15  4541.3 1612.47  4609.0 1611.99  4626.4 1611.34  4650.8 1610.07
  4746.0 1608.12  4809.4 1607.86  4822.4 1607.04  4894.0 1605.82  4916.0 1604.51
  4942.0 1605.14  4947.3 1605.70  4978.6 1604.79  5000.8 1605.02  5017.8 1604.30
  5018.1 1603.80  5021.7 1603.80  5022.0 1604.30  5040.2 1605.22  5073.2 1605.99
  5080.8 1607.57  5151.8 1609.11  5222.7 1612.45  5249.7 1613.54  5254.7 1613.28
  5375.8 1618.63  5385.0 1619.69  5410.5 1620.85  5431.2 1622.22  5466.9 1622.35
#Mann=5,-1,0
  4484.6   0.045       0  4626.4    0.16       0  5017.8    0.07       0
  5022.0    0.16       0  5410.5    0.07       0
Bank Sta=5017.8,5022
Exp/Cntr=0.3,0.1

Type RM Length L Ch R = 1,11822,446,446,446
BEGIN DESCRIPTION:
Mapping XS 442e4372
END DESCRIPTION:
XS GIS Cut Line= 3
      1592089.22      6972542.49      1591858.32      6971981.72
      1591705.90      6971592.02
#Sta/Elev= 30
  4395.3 1614.42  4500.6 1612.71  4524.6 1611.72  4572.4 1610.77  4626.3 1610.19
  4703.0 1609.84  4708.4 1609.17  4763.5 1607.83  4876.0 1604.21  4951.7 1603.99
  4974.9 1604.59  4984.1 1604.18  4991.3 1601.79  4991.6 1601.29  4995.3 1601.29
  4995.5 1601.79  4998.8 1602.54  5001.1 1603.82  5023.2 1604.32  5028.6 1603.99
  5059.4 1604.19  5087.9 1604.86  5161.6 1610.14  5172.8 1610.56  5275.6 1614.77
  5300.1 1615.32  5306.4 1616.22  5338.6 1617.28  5390.2 1621.26  5420.2 1623.46
#Mann=8,-1,0
  4395.3   0.045       0  4626.3    0.07       0  4763.5    0.16       0
  4991.3    0.07       0  4995.5    0.16       0  5087.9    0.07       0
  5172.8    0.16       0  5390.2    0.07       0
Bank Sta=4991.3,4995.5
Exp/Cntr=0.3,0.1

Type RM Length L Ch R = 1,11376,456,456,456
BEGIN DESCRIPTION:
Mapping XS 7f52870e
END DESCRIPTION:
XS GIS Cut Line= 3
      1592261.09      6972521.67      1592250.68      6972032.06
      1592129.15      6971589.36
#Sta/Elev= 30
  4512.2 1612.58  4775.9 1609.20  4811.8 1607.26  4876.0 1605.12  4896.0 1603.96
  4946.0 1603.44  4966.0 1601.22  4976.0 1601.57  4996.0 1601.07  5025.1 1601.57
  5037.2 1601.26  5042.3 1600.58  5051.9 1601.04  5068.4 1600.80  5074.6 1600.14
  5074.9 1599.64  5078.6 1599.64  5078.9 1600.14  5082.0 1600.99  5089.1 1600.38
  5109.8 1601.64  5150.9 1601.76  5195.7 1602.53  5230.1 1605.47  5264.6 1607.43
  5342.5 1610.20  5383.4 1611.35  5389.8 1612.00  5452.0 1614.11  5461.0 1614.90
#Mann=7,-1,0
  4512.2   0.045       0  4811.8    0.07       0  5025.1    0.16       0
  5051.9    0.07       0  5074.6    0.07       0  5078.9    0.07       0
  5342.5   0.035       0
Bank Sta=5074.6,5078.9
Exp/Cntr=0.3,0.1

Type RM Length L Ch R = 1,10920,308,308,308
BEGIN DESCRIPTION:
Mapping XS c9c392cb
END DESCRIPTION:
XS GIS Cut Line= 3
      1592686.96      6972257.50      1592477.56      6971863.66
      1592218.55      6971647.82
#Sta/Elev= 30
  4554.0 1610.03  4558.1 1610.08  4591.6 1609.66  4613.6 1608.01  4666.7 1606.93
  4673.8 1606.09  4756.1 1603.16  4768.6 1601.88  4800.0 1601.15  4805.7 1601.83
  4813.9 1600.99  4859.2 1600.48  4893.6 1600.81  4904.3 1600.59  4909.9 1599.41
  4915.8 1600.60  4926.2 1600.40  4931.9 1599.44  4938.5 1600.41  4953.9 1600.25
  4992.2 1599.68  5003.3 1598.71  5003.6 1598.21  5007.7 1598.71  5034.1 1601.20
  5077.1 1601.23  5105.7 1603.02  5147.4 1603.94  5257.5 1608.64  5337.2 1611.38
#Mann=5,-1,0
  4554.0   0.045       0  4558.1    0.07       0  5003.3    0.07       0
  5007.7    0.07       0  5257.5   0.035       0
Bank Sta=5003.3,5007.7
Exp/Cntr=0.3,0.1

Type RM Length L Ch R = 1,10612,224,224,224
BEGIN DESCRIPTION:
Mapping XS f29fab40
END DESCRIPTION:
XS GIS Cut Line= 3
      1592866.01      6972206.51      1592726.05      6971866.91
      1592314.80      6971656.41
#Sta/Elev= 30
  4632.9 1609.50  4754.7 1607.38  4861.2 1600.59  4901.7 1599.59  4977.4 1599.19
  4991.7 1598.35  4996.9 1599.47  5003.6 1599.47  5007.9 1597.66  5011.3 1597.31
  5011.6 1596.81  5015.4 1596.81  5015.7 1597.31  5030.1 1598.66  5035.7 1598.00
  5046.3 1597.94  5057.9 1599.41  5068.8 1599.76  5102.5 1599.72  5135.5 1600.55
  5185.6 1600.97  5192.4 1601.43  5224.4 1600.63  5237.3 1601.37  5268.8 1601.82
  5274.4 1602.57  5296.6 1602.28  5372.1 1604.72  5431.4 1607.59  5462.2 1609.01
#Mann=4,-1,0
  4632.9    0.07       0  5011.3    0.07       0  5015.7    0.07       0
  5431.4   0.035       0
Bank Sta=5011.3,5015.7
Exp/Cntr=0.3,0.1

Type RM Length L Ch R = 1,10388,310,310,310
BEGIN DESCRIPTION:
Mapping XS 51f4e181
END DESCRIPTION:
XS GIS Cut Line= 6
      1592912.59      6972043.35      1592911.29      6971832.38
      1592891.76      6971734.72      1592816.24      6971676.13
      1592740.72      6971630.56      1592378.02      6971620.20
#Sta/Elev= 30
  4594.3 1606.64  4689.7 1604.99  4719.7 1604.95  4729.7 1604.42  4769.7 1604.01
  4799.7 1603.07  4805.0 1602.40  4808.6 1602.40  4813.3 1601.65  4840.3 1596.35
  4864.3 1595.85  4919.7 1595.76  4920.0 1595.26  4923.8 1595.26  4924.1 1595.76
  4950.8 1595.90  4957.2 1596.26  4986.1 1596.23  4992.5 1598.78  5028.5 1598.71
  5086.3 1599.81  5154.4 1600.19  5184.4 1601.06  5254.4 1601.95  5284.4 1603.04
  5349.5 1604.56  5356.4 1605.38  5384.5 1605.89  5435.8 1607.66  5451.5 1608.20
#Mann=4,-1,0
  4594.3    0.07       0  4919.7    0.07       0  4924.1    0.07       0
  5435.8   0.035       0
Bank Sta=4919.7,4924.1
Exp/Cntr=0.3,0.1

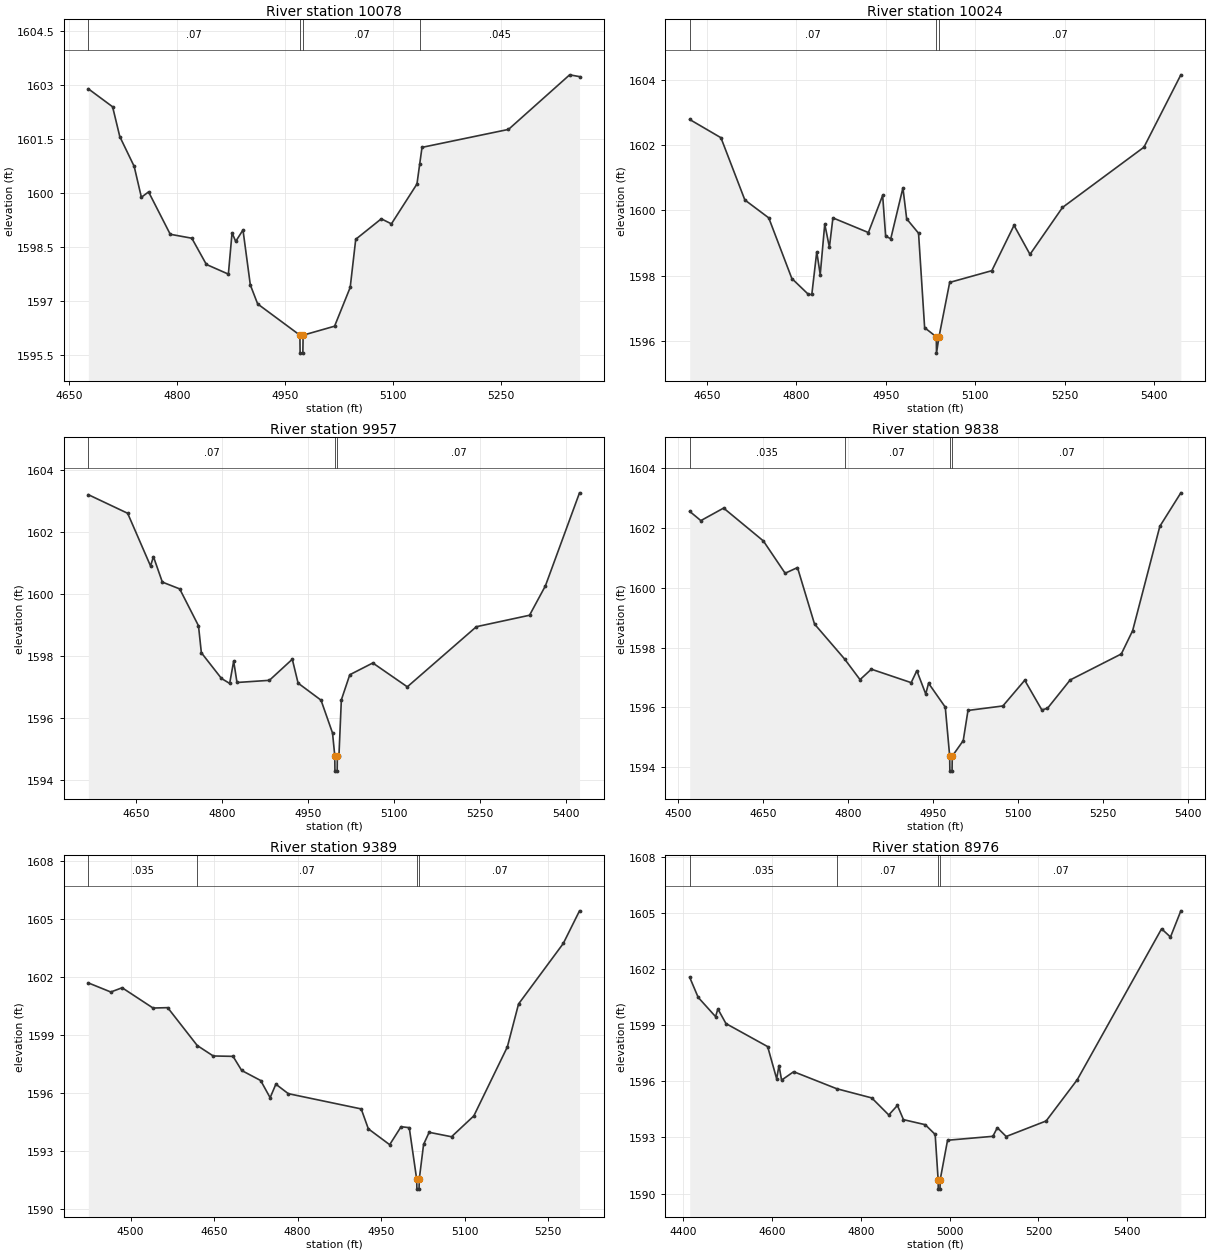
Type RM Length L Ch R = 1,10078,54,54,54
BEGIN DESCRIPTION:
Mapping XS 99c4866d
END DESCRIPTION:
XS GIS Cut Line= 6
      1593048.79      6971841.62      1593040.98      6971690.63
      1593059.21      6971594.27      1593072.23      6971520.05
      1593025.35      6971504.43      1592800.11      6971293.51
#Sta/Elev= 30
  4676.4 1602.90  4710.1 1602.40  4720.1 1601.57  4740.1 1600.74  4750.1 1599.88
  4760.1 1600.03  4790.2 1598.85  4820.2 1598.74  4840.4 1598.01  4871.0 1597.74
  4876.1 1598.89  4881.2 1598.65  4891.3 1598.97  4901.5 1597.44  4911.7 1596.91
  4970.4 1596.04  4970.7 1595.54  4974.5 1595.54  4974.9 1596.04  5018.6 1596.29
  5040.3 1597.37  5048.0 1598.71  5083.5 1599.28  5097.6 1599.14  5133.1 1600.25
  5137.0 1600.82  5140.1 1601.27  5260.3 1601.77  5345.3 1603.29  5359.0 1603.24
#Mann=4,-1,0
  4676.4    0.07       0  4970.4    0.07       0  4974.9    0.07       0
  5137.0   0.045       0
Bank Sta=4970.4,4974.9
Exp/Cntr=0.3,0.1

Type RM Length L Ch R = 1,10024,67,67,67
BEGIN DESCRIPTION:
Mapping XS 4c096113
END DESCRIPTION:
XS GIS Cut Line= 6
      1593070.92      6971840.38      1593081.34      6971639.85
      1593132.12      6971557.81      1593128.22      6971507.03
      1593109.99      6971482.29      1592973.25      6971059.07
#Sta/Elev= 30
  4621.3 1602.79  4673.7 1602.23  4713.8 1600.32  4753.9 1599.77  4792.6 1597.91
  4820.5 1597.42  4826.1 1597.42  4834.4 1598.73  4840.2 1598.03  4847.8 1599.58
  4855.6 1598.87  4861.5 1599.77  4921.0 1599.32  4944.9 1600.46  4949.9 1599.21
  4958.5 1599.13  4978.9 1600.69  4985.2 1599.74  5005.1 1599.30  5015.3 1596.40
  5034.9 1596.12  5035.2 1595.62  5039.4 1596.12  5057.3 1597.79  5128.0 1598.15
  5165.2 1599.54  5192.0 1598.65  5246.5 1600.09  5383.1 1601.94  5445.0 1604.16
#Mann=3,-1,0
  4621.3    0.07       0  5034.9    0.07       0  5039.4    0.07       0
Bank Sta=5034.9,5039.4
Exp/Cntr=0.3,0.1

Type RM Length L Ch R = 1,9957,119,119,119
BEGIN DESCRIPTION:
Mapping XS d545da9b
END DESCRIPTION:
XS GIS Cut Line= 5
      1593085.24      6971856.02      1593111.29      6971658.08
      1593168.58      6971564.33      1593160.77      6971440.63
      1593121.71      6971018.79
#Sta/Elev= 30
  4566.5 1603.21  4635.1 1602.61  4675.0 1600.91  4680.1 1601.21  4695.6 1600.39
  4725.9 1600.17  4758.7 1598.98  4763.7 1598.11  4798.8 1597.28  4813.1 1597.12
  4820.1 1597.84  4825.9 1597.15  4882.4 1597.22  4922.4 1597.90  4932.5 1597.13
  4972.5 1596.58  4992.6 1595.52  4996.5 1594.79  4996.8 1594.29  5000.7 1594.29
  5001.0 1594.79  5003.8 1594.79  5008.0 1596.59  5022.7 1597.40  5062.9 1597.78
  5123.1 1597.01  5243.6 1598.95  5336.4 1599.32  5364.1 1600.27  5423.6 1603.27
#Mann=3,-1,0
  4566.5    0.07       0  4996.5    0.07       0  5001.0    0.07       0
Bank Sta=4996.5,5001
Exp/Cntr=0.3,0.1

Type RM Length L Ch R = 1,9838,449,449,449
BEGIN DESCRIPTION:
Mapping XS 3922a70a
END DESCRIPTION:
XS GIS Cut Line= 3
      1593303.99      6971867.68      1593264.93      6971389.85
      1593237.59      6971003.14
#Sta/Elev= 30
  4520.6 1602.56  4540.3 1602.25  4580.5 1602.67  4650.7 1601.57  4689.1 1600.49
  4710.9 1600.68  4741.0 1598.79  4794.1 1597.62  4821.3 1596.93  4841.3 1597.28
  4911.6 1596.83  4921.6 1597.23  4937.3 1596.45  4942.3 1596.81  4971.8 1596.01
  4979.6 1594.37  4979.9 1593.87  4983.8 1593.87  4984.1 1594.37  5003.5 1594.89
  5011.9 1595.90  5073.5 1596.05  5112.1 1596.91  5142.2 1595.92  5152.2 1595.97
  5192.3 1596.92  5282.6 1597.79  5302.6 1598.57  5350.6 1602.06  5387.7 1603.18
#Mann=4,-1,0
  4520.6   0.035       0  4794.1    0.07       0  4979.6    0.07       0
  4984.1    0.07       0
Bank Sta=4979.6,4984.1
Exp/Cntr=0.3,0.1

Type RM Length L Ch R = 1,9389,413,413,413
BEGIN DESCRIPTION:
Mapping XS 3b9765dc
END DESCRIPTION:
XS GIS Cut Line= 3
      1593386.03      6971797.41      1593505.82      6971233.60
      1593479.89      6970928.90
#Sta/Elev= 30
  4424.1 1601.71  4464.4 1601.24  4484.8 1601.46  4540.3 1600.41  4566.6 1600.43
  4619.7 1598.47  4648.4 1597.93  4684.0 1597.91  4699.5 1597.18  4733.6 1596.66
  4750.6 1595.77  4760.9 1596.47  4783.2 1595.98  4914.2 1595.19  4927.0 1594.16
  4965.3 1593.34  4985.8 1594.27  5000.5 1594.22  5013.9 1591.54  5014.2 1591.04
  5018.1 1591.04  5018.4 1591.54  5026.2 1593.35  5036.2 1593.98  5076.4 1593.75
  5116.5 1594.83  5176.7 1598.40  5196.8 1600.62  5277.1 1603.75  5306.3 1605.44
#Mann=4,-1,0
  4424.1   0.035       0  4619.7    0.07       0  5013.9    0.07       0
  5018.4    0.07       0
Bank Sta=5013.9,5018.4
Exp/Cntr=0.3,0.1

Type RM Length L Ch R = 1,8976,264,264,264
BEGIN DESCRIPTION:
Mapping XS 54ece326
END DESCRIPTION:
XS GIS Cut Line= 3
      1593592.51      6971896.27      1593760.92      6971333.75
      1593759.18      6970814.64
#Sta/Elev= 30
  4414.4 1601.55  4433.5 1600.48  4472.7 1599.45  4477.9 1599.86  4496.1 1599.08
  4590.0 1597.85  4610.3 1596.13  4615.5 1596.84  4621.4 1596.06  4648.6 1596.51
  4745.7 1595.60  4824.5 1595.11  4862.8 1594.20  4882.3 1594.71  4895.9 1593.95
  4945.0 1593.68  4967.3 1593.16  4974.0 1590.74  4974.3 1590.24  4978.2 1590.24
  4978.6 1590.74  4995.2 1592.85  5097.3 1593.06  5107.3 1593.52  5127.3 1593.05
  5217.3 1593.88  5287.3 1596.08  5477.3 1604.14  5497.3 1603.70  5520.7 1605.10
#Mann=4,-1,0
  4414.4   0.035       0  4745.7    0.07       0  4974.0    0.07       0
  4978.6    0.07       0
Bank Sta=4974,4978.6
Exp/Cntr=0.3,0.1

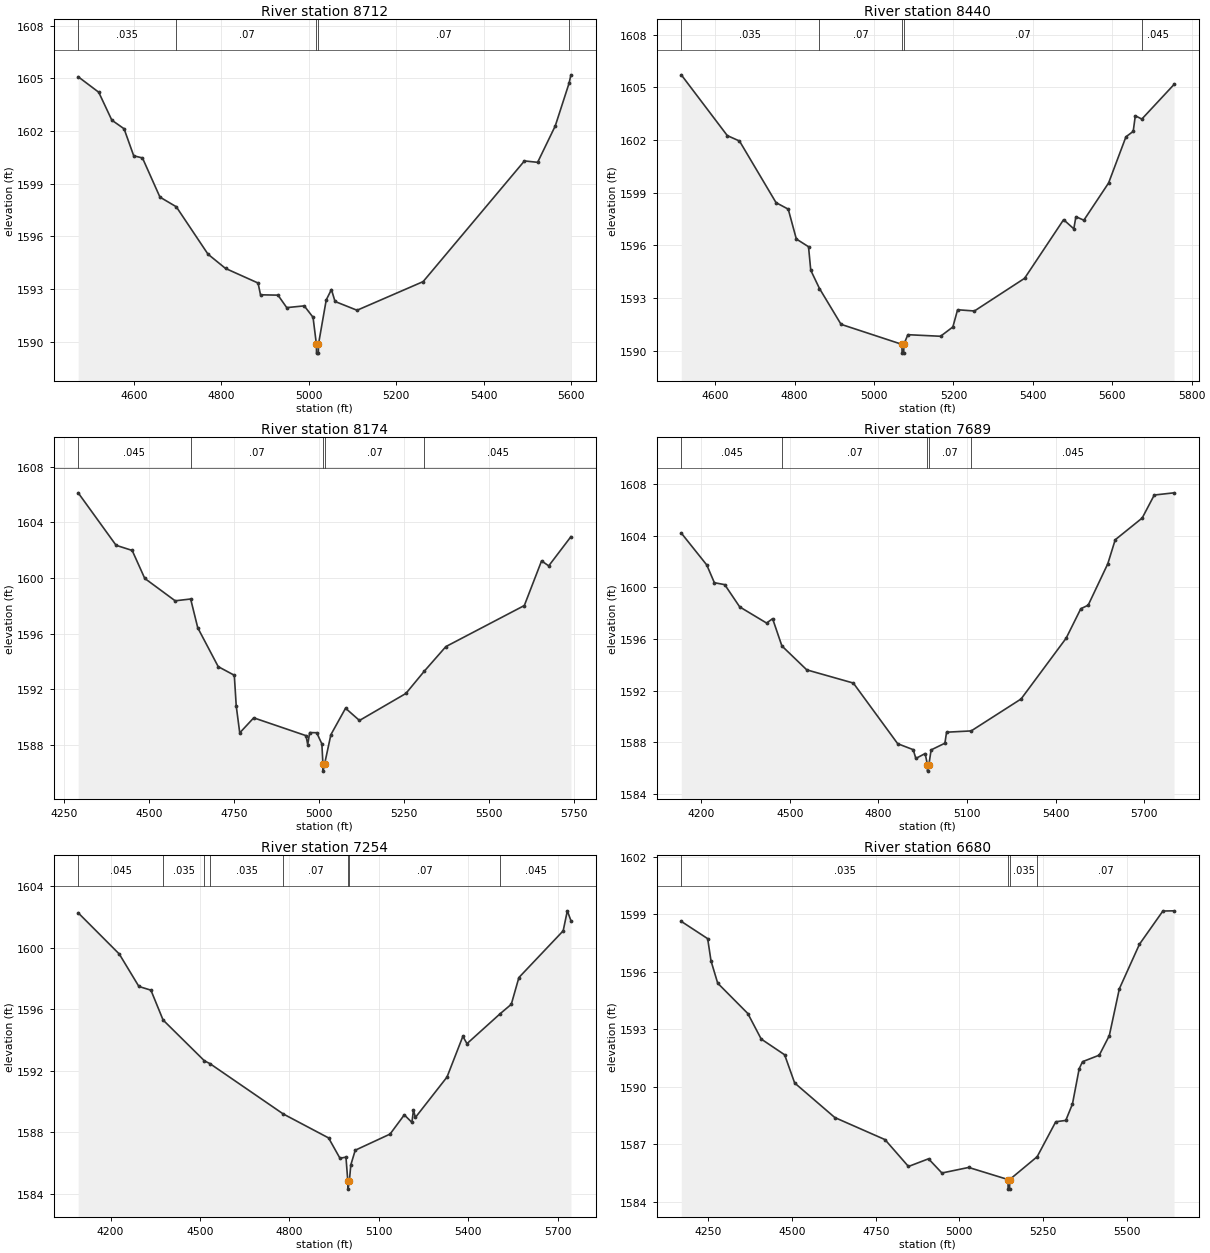
Type RM Length L Ch R = 1,8712,272,272,272
BEGIN DESCRIPTION:
Mapping XS 8c55ab84
END DESCRIPTION:
XS GIS Cut Line= 3
      1593993.56      6971864.99      1593976.20      6971338.96
      1593901.63      6970742.41
#Sta/Elev= 30
  4472.2 1605.09  4519.2 1604.21  4549.2 1602.62  4577.2 1602.13  4599.3 1600.59
  4619.3 1600.47  4659.3 1598.24  4696.7 1597.69  4769.3 1594.99  4809.4 1594.18
  4883.8 1593.35  4889.4 1592.68  4929.4 1592.66  4949.4 1591.95  4989.5 1592.05
  5009.6 1591.40  5017.3 1589.86  5017.6 1589.36  5021.7 1589.36  5022.0 1589.86
  5039.8 1592.39  5051.7 1592.98  5059.9 1592.30  5110.3 1591.80  5261.5 1593.43
  5493.3 1600.30  5523.5 1600.22  5563.8 1602.29  5595.4 1604.72  5599.7 1605.20
#Mann=5,-1,0
  4472.2   0.035       0  4696.7    0.07       0  5017.3    0.07       0
  5022.0    0.07       0  5595.4   0.045       0
Bank Sta=5017.3,5022
Exp/Cntr=0.3,0.1

Type RM Length L Ch R = 1,8440,266,266,266
BEGIN DESCRIPTION:
Mapping XS 7af52e5d
END DESCRIPTION:
XS GIS Cut Line= 3
      1594299.12      6971771.27      1594194.95      6971290.35
      1593946.69      6970583.76
#Sta/Elev= 30
  4514.6 1605.72  4630.5 1602.26  4661.2 1601.95  4753.3 1598.44  4784.0 1598.07
  4804.4 1596.37  4835.1 1595.93  4840.7 1594.59  4862.7 1593.55  4917.0 1591.51
  5070.4 1590.37  5070.7 1589.87  5074.8 1589.87  5075.2 1590.37  5085.3 1590.92
  5167.6 1590.83  5198.6 1591.36  5210.5 1592.34  5252.9 1592.27  5379.2 1594.13
  5477.5 1597.47  5503.2 1596.95  5508.5 1597.64  5528.5 1597.44  5590.8 1599.56
  5634.5 1602.19  5652.8 1602.50  5658.1 1603.39  5674.5 1603.20  5755.6 1605.17
#Mann=5,-1,0
  4514.6   0.035       0  4862.7    0.07       0  5070.4    0.07       0
  5075.2    0.07       0  5674.5   0.045       0
Bank Sta=5070.4,5075.2
Exp/Cntr=0.3,0.1

Type RM Length L Ch R = 1,8174,485,485,485
BEGIN DESCRIPTION:
Mapping XS 433b4de9
END DESCRIPTION:
XS GIS Cut Line= 3
      1594516.14      6971779.97      1594351.20      6971087.22
      1594127.24      6970385.82
#Sta/Elev= 30
  4291.9 1606.12  4403.3 1602.35  4450.6 1601.98  4487.6 1599.97  4577.0 1598.36
  4622.5 1598.49  4643.4 1596.42  4703.5 1593.63  4750.8 1593.01  4756.5 1590.80
  4766.8 1588.87  4807.9 1589.95  4961.5 1588.67  4966.6 1588.03  4972.4 1588.89
  4992.9 1588.88  5008.2 1588.08  5011.3 1586.62  5011.6 1586.12  5016.1 1586.62
  5034.7 1588.74  5077.8 1590.64  5118.7 1589.76  5255.1 1591.70  5309.2 1593.30
  5372.7 1595.07  5603.3 1598.02  5654.0 1601.23  5675.0 1600.87  5740.3 1602.97
#Mann=5,-1,0
  4291.9   0.045       0  4622.5    0.07       0  5011.3    0.07       0
  5016.1    0.07       0  5309.2   0.045       0
Bank Sta=5011.3,5016.1
Exp/Cntr=0.3,0.1

Type RM Length L Ch R = 1,7689,435,435,435
BEGIN DESCRIPTION:
Mapping XS e2ef7c29
END DESCRIPTION:
XS GIS Cut Line= 3
      1594838.04      6971753.30      1594699.14      6970898.24
      1594421.36      6970145.20
#Sta/Elev= 30
  4132.4 1604.19  4218.8 1601.72  4244.5 1600.35  4279.6 1600.20  4330.3 1598.48
  4421.4 1597.23  4441.7 1597.57  4473.2 1595.46  4557.5 1593.61  4715.2 1592.59
  4865.4 1587.90  4917.9 1587.44  4926.9 1586.76  4958.4 1587.14  4966.1 1586.28
  4966.4 1585.78  4971.0 1586.28  4978.6 1587.42  5025.3 1587.94  5030.9 1588.79
  5114.4 1588.89  5283.3 1591.36  5435.9 1596.06  5485.6 1598.34  5510.5 1598.61
  5576.9 1601.81  5602.1 1603.67  5693.4 1605.35  5734.4 1607.13  5801.3 1607.30
#Mann=5,-1,0
  4132.4   0.045       0  4473.2    0.07       0  4966.1    0.07       0
  4971.0    0.07       0  5114.4   0.045       0
Bank Sta=4966.1,4971
Exp/Cntr=0.3,0.1

Type RM Length L Ch R = 1,7254,574,574,574
BEGIN DESCRIPTION:
Mapping XS 5d3350a2
END DESCRIPTION:
XS GIS Cut Line= 3
      1595165.73      6971690.37      1595061.56      6970785.40
      1594811.98      6970086.57
#Sta/Elev= 30
  4091.3 1602.26  4229.2 1599.58  4295.0 1597.47  4335.3 1597.23  4376.1 1595.29
  4515.0 1592.63  4532.7 1592.46  4779.1 1589.18  4931.3 1587.62  4969.4 1586.30
  4989.6 1586.37  4995.9 1584.79  4996.3 1584.29  5000.9 1584.79  5005.8 1585.86
  5020.7 1586.82  5137.5 1587.87  5185.3 1589.12  5210.8 1588.63  5216.1 1589.44
  5222.5 1588.95  5328.6 1591.58  5381.8 1594.23  5395.5 1593.75  5507.0 1595.70
  5544.2 1596.31  5569.7 1598.05  5718.3 1601.09  5732.2 1602.39  5744.3 1601.75
#Mann=8,-1,0
  4091.3   0.045       0  4376.1   0.035       0  4515.0    0.07       0
  4532.7   0.035       0  4779.1    0.07       0  4995.9    0.07       0
  5000.9    0.07       0  5507.0   0.045       0
Bank Sta=4995.9,5000.9
Exp/Cntr=0.3,0.1

Type RM Length L Ch R = 1,6680,209,209,209
BEGIN DESCRIPTION:
Mapping XS cbecc929
END DESCRIPTION:
XS GIS Cut Line= 3
      1595536.73      6971516.88      1595548.88      6970687.05
      1595524.58      6970044.73
#Sta/Elev= 30
  4168.8 1598.62  4247.7 1597.72  4257.7 1596.56  4277.7 1595.40  4367.7 1593.82
  4407.7 1592.49  4477.7 1591.67  4507.7 1590.20  4627.7 1588.40  4777.7 1587.25
  4847.8 1585.85  4907.8 1586.25  4947.8 1585.51  5027.8 1585.80  5145.3 1585.17
  5145.7 1584.67  5150.0 1584.67  5150.4 1585.17  5232.5 1586.36  5288.0 1588.18
  5318.0 1588.25  5338.0 1589.11  5358.0 1590.94  5368.0 1591.31  5418.1 1591.65
  5448.1 1592.67  5478.1 1595.11  5538.2 1597.43  5608.2 1599.16  5641.5 1599.17
#Mann=4,-1,0
  4168.8   0.035       0  5145.3   0.035       0  5150.4   0.035       0
  5232.5    0.07       0
Bank Sta=5145.3,5150.4
Exp/Cntr=0.3,0.1