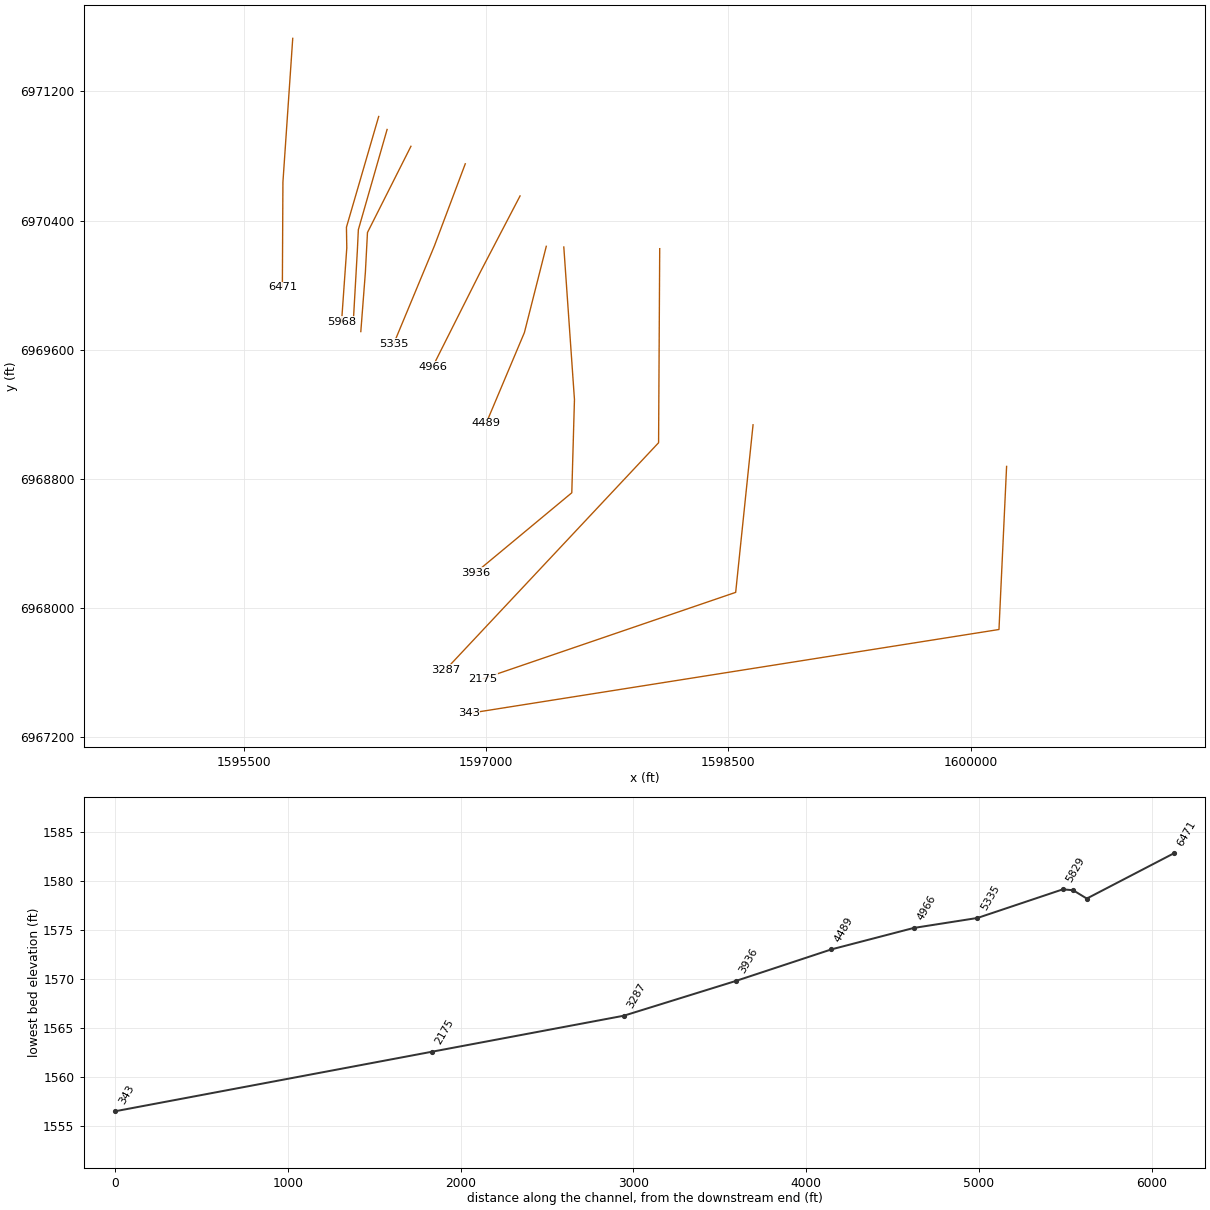
HEC-RAS study Chimney Creek 1201.prj: Chimney Creek 1201 Base Level Engineering

--- Chimney Creek 1201.g01 (geometry) --- (continued)

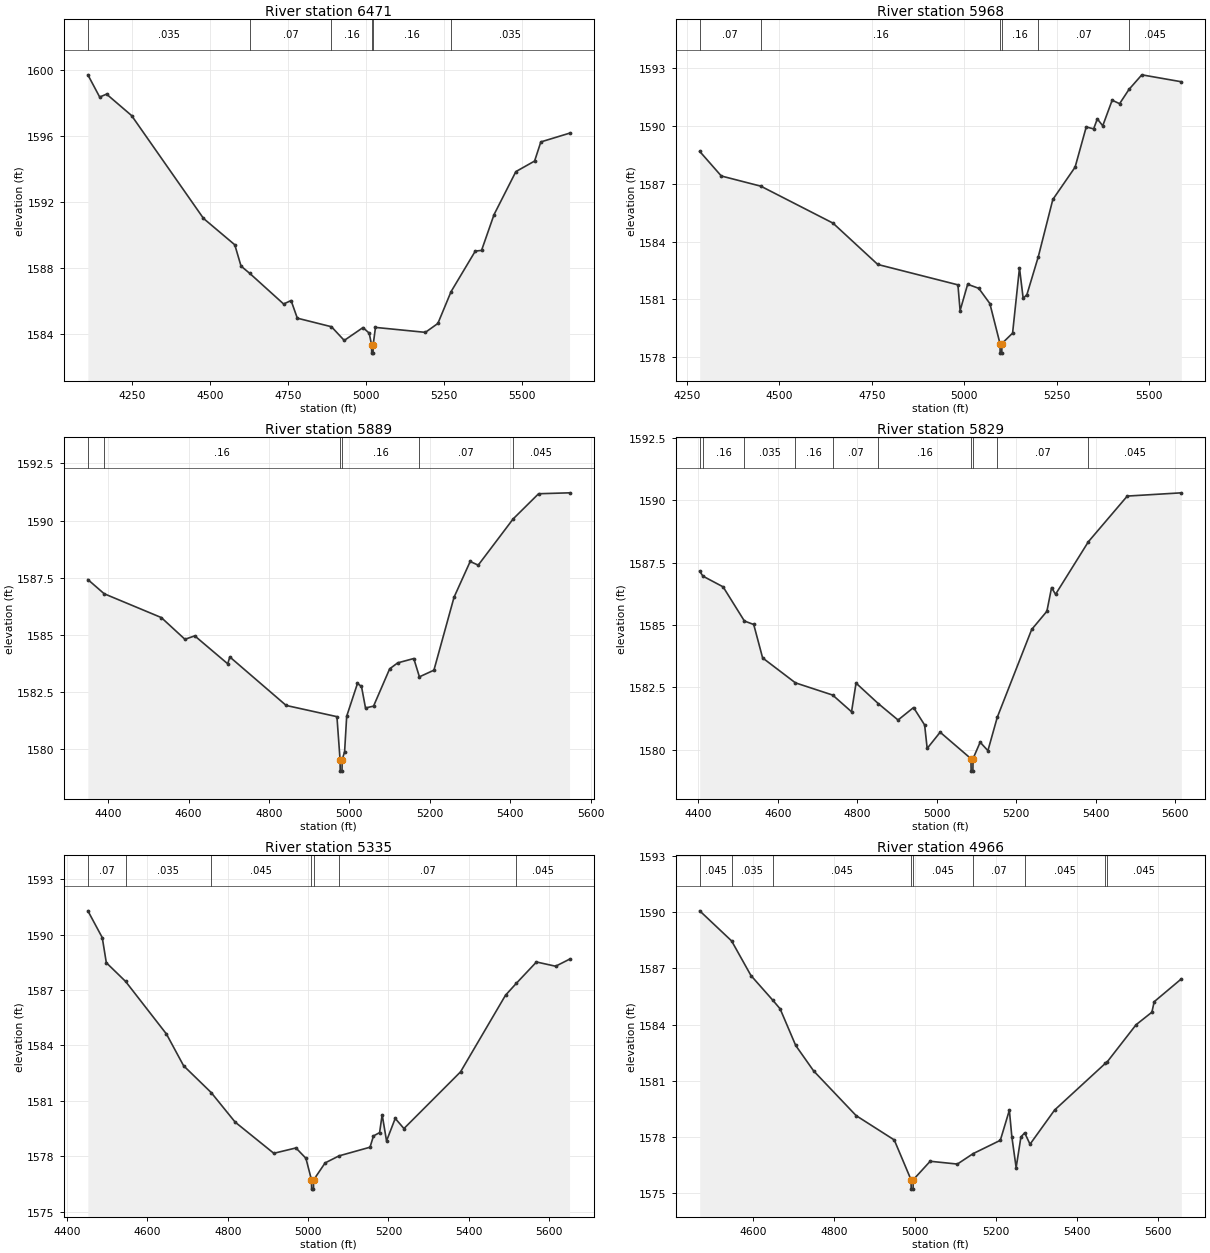
Type RM Length L Ch R = 1,6471,503,503,503
BEGIN DESCRIPTION:
Mapping XS 41c751f6
END DESCRIPTION:
XS GIS Cut Line= 3
      1595802.79      6971527.76      1595742.03      6970637.13
      1595738.55      6969986.14
#Sta/Elev= 30
  4108.5 1599.69  4146.4 1598.34  4168.4 1598.52  4248.6 1597.22  4479.1 1590.98
  4579.4 1589.38  4599.4 1588.09  4627.8 1587.64  4735.9 1585.79  4759.8 1586.00
  4779.8 1584.93  4889.3 1584.41  4930.2 1583.58  4990.3 1584.36  5010.3 1584.02
  5017.8 1583.31  5018.2 1582.81  5022.5 1582.81  5022.9 1583.31  5030.3 1584.37
  5190.3 1584.07  5230.3 1584.61  5272.6 1586.54  5350.3 1589.00  5370.3 1589.04
  5410.3 1591.21  5480.3 1593.82  5540.3 1594.46  5560.3 1595.62  5652.2 1596.15
#Mann=6,-1,0
  4108.5   0.035       0  4627.8    0.07       0  4889.3    0.16       0
  5017.8    0.07       0  5022.9    0.16       0  5272.6   0.035       0
Bank Sta=5017.8,5022.9
Exp/Cntr=0.3,0.1

Type RM Length L Ch R = 1,5968,79,79,79
BEGIN DESCRIPTION:
Mapping XS 0f287f08
END DESCRIPTION:
XS GIS Cut Line= 4
      1596334.91      6971043.96      1596135.25      6970358.15
      1596137.42      6970230.12      1596104.97      6969771.50
#Sta/Elev= 30
  4284.8 1588.69  4343.2 1587.41  4450.1 1586.88  4645.1 1584.96  4766.2 1582.81
  4982.9 1581.75  4988.8 1580.41  5009.2 1581.78  5039.2 1581.57  5069.2 1580.78
  5096.6 1578.70  5097.1 1578.20  5101.5 1578.20  5101.9 1578.70  5130.7 1579.24
  5149.3 1582.63  5159.3 1581.05  5169.4 1581.24  5200.3 1583.22  5239.5 1586.19
  5299.7 1587.87  5329.8 1589.96  5349.8 1589.86  5359.8 1590.38  5374.4 1590.02
  5399.9 1591.35  5420.0 1591.17  5445.3 1591.91  5480.1 1592.67  5586.9 1592.31
#Mann=6,-1,0
  4284.8    0.07       0  4450.1    0.16       0  5096.6    0.07       0
  5101.9    0.16       0  5200.3    0.07       0  5445.3   0.045       0
Bank Sta=5096.6,5101.9
Exp/Cntr=0.3,0.1

Type RM Length L Ch R = 1,5889,60,60,60
BEGIN DESCRIPTION:
Mapping XS 4908204f
END DESCRIPTION:
XS GIS Cut Line= 4
      1596386.98      6970963.62      1596209.03      6970342.96
      1596202.52      6970208.42      1596178.75      6969791.26
#Sta/Elev= 30
  4349.4 1587.42  4390.0 1586.80  4532.1 1585.76  4590.9 1584.81  4615.3 1584.96
  4697.3 1583.74  4702.5 1584.04  4842.7 1581.92  4969.0 1581.43  4976.8 1579.55
  4977.2 1579.05  4981.6 1579.05  4982.1 1579.55  4988.1 1579.90  4993.3 1581.45
  5020.1 1582.88  5030.1 1582.75  5040.1 1581.81  5060.1 1581.89  5100.2 1583.52
  5120.2 1583.78  5160.2 1583.97  5174.2 1583.17  5210.3 1583.46  5260.4 1586.65
  5300.5 1588.21  5320.5 1588.05  5407.4 1590.07  5470.7 1591.17  5547.6 1591.21
#Mann=6,-1,0
  4349.4    0.07       0  4390.0    0.16       0  4976.8    0.07       0
  4982.1    0.16       0  5174.2    0.07       0  5407.4   0.045       0
Bank Sta=4976.8,4982.1
Exp/Cntr=0.3,0.1

Type RM Length L Ch R = 1,5829,494,494,494
BEGIN DESCRIPTION:
Mapping XS 12a81528
END DESCRIPTION:
XS GIS Cut Line= 4
      1596534.55      6970859.45      1596265.46      6970325.60
      1596252.43      6970078.21      1596224.28      6969712.26
#Sta/Elev= 30
  4403.2 1587.16  4411.2 1586.96  4462.1 1586.53  4515.7 1585.16  4539.2 1585.02
  4561.6 1583.68  4644.2 1582.68  4738.0 1582.19  4785.5 1581.52  4796.8 1582.67
  4852.7 1581.85  4902.6 1581.19  4941.6 1581.69  4969.5 1580.99  4975.9 1580.05
  5008.6 1580.70  5086.1 1579.64  5086.6 1579.14  5091.0 1579.14  5091.4 1579.64
  5109.3 1580.30  5128.8 1579.96  5152.4 1581.30  5239.0 1584.82  5277.3 1585.55
  5289.1 1586.50  5299.1 1586.23  5381.8 1588.34  5479.7 1590.17  5615.8 1590.30
#Mann=10,-1,0
  4403.2    0.07       0  4411.2    0.16       0  4515.7   0.035       0
  4644.2    0.16       0  4738.0    0.07       0  4852.7    0.16       0
  5086.1    0.07       0  5091.4    0.16       0  5152.4    0.07       0
  5381.8   0.045       0
Bank Sta=5086.1,5091.4
Exp/Cntr=0.3,0.1

Type RM Length L Ch R = 1,5335,369,369,369
BEGIN DESCRIPTION:
Mapping XS ef3d145d
END DESCRIPTION:
XS GIS Cut Line= 3
      1596870.94      6970750.99      1596679.95      6970243.14
      1596428.21      6969637.66
#Sta/Elev= 30
  4452.1 1591.29  4487.9 1589.84  4498.0 1588.48  4545.8 1587.47  4647.6 1584.62
  4690.3 1582.90  4758.9 1581.45  4818.5 1579.85  4914.7 1578.16  4969.8 1578.45
  4994.6 1577.89  5008.4 1576.72  5008.8 1576.22  5013.4 1576.22  5013.8 1576.72
  5042.4 1577.64  5076.9 1578.02  5154.1 1578.49  5162.7 1579.10  5177.9 1579.28
  5184.3 1580.25  5195.2 1578.83  5216.8 1580.05  5238.5 1579.50  5379.3 1582.57
  5491.2 1586.72  5517.9 1587.36  5568.2 1588.52  5615.9 1588.29  5650.4 1588.67
#Mann=7,-1,0
  4452.1    0.07       0  4545.8   0.035       0  4758.9   0.045       0
  5008.4   0.045       0  5013.8   0.045       0  5076.9    0.07       0
  5517.9   0.045       0
Bank Sta=5008.4,5013.8
Exp/Cntr=0.3,0.1

Type RM Length L Ch R = 1,4966,477,477,477
BEGIN DESCRIPTION:
Mapping XS fa6a994c
END DESCRIPTION:
XS GIS Cut Line= 3
      1597210.09      6970552.03      1596963.55      6970079.77
      1596669.21      6969494.56
#Sta/Elev= 30
  4468.7 1590.08  4547.4 1588.47  4595.1 1586.62  4649.4 1585.29  4667.0 1584.84
  4705.5 1582.88  4749.7 1581.52  4854.5 1579.13  4948.5 1577.83  4989.9 1575.70
  4990.3 1575.20  4994.9 1575.20  4995.3 1575.70  5037.1 1576.69  5104.2 1576.54
  5143.2 1577.10  5210.1 1577.81  5232.4 1579.42  5238.5 1578.00  5249.1 1576.35
  5260.9 1577.99  5270.2 1578.21  5283.3 1577.60  5344.0 1579.43  5468.9 1581.92
  5473.9 1582.01  5544.9 1583.99  5583.9 1584.66  5589.5 1585.22  5656.5 1586.44
#Mann=9,-1,0
  4468.7   0.045       0  4547.4   0.035       0  4649.4   0.045       0
  4989.9   0.045       0  4995.3   0.045       0  5143.2    0.07       0
  5270.2   0.045       0  5468.9    0.07       0  5473.9   0.045       0
Bank Sta=4989.9,4995.3
Exp/Cntr=0.3,0.1

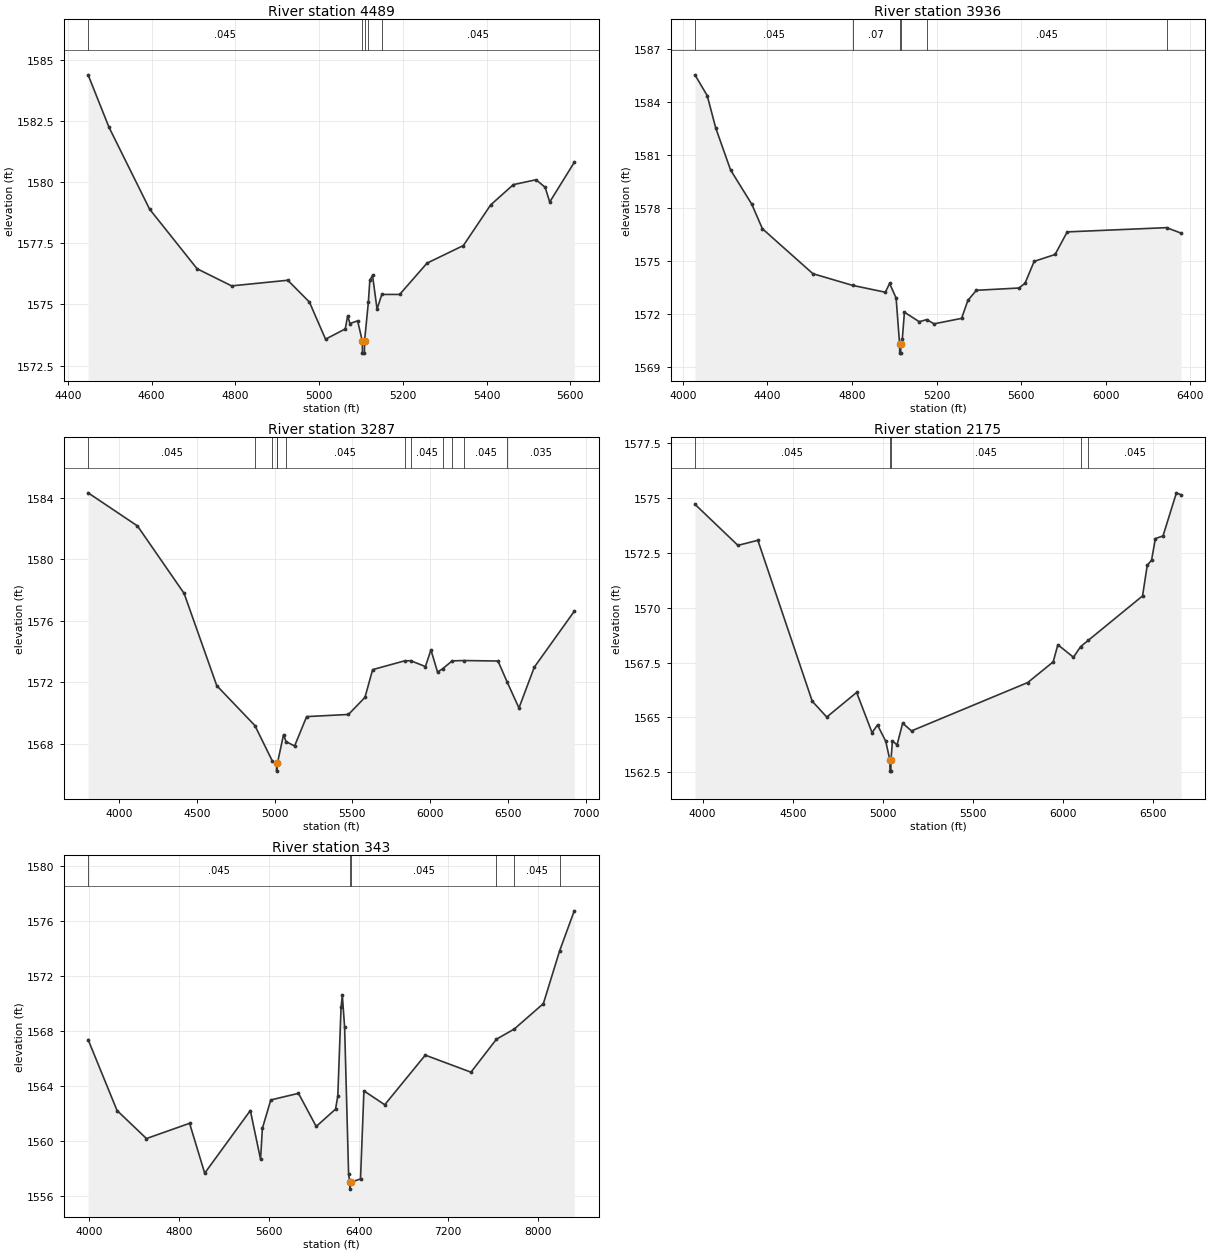
Type RM Length L Ch R = 1,4489,553,553,553
BEGIN DESCRIPTION:
Mapping XS 2b91549f
END DESCRIPTION:
XS GIS Cut Line= 3
      1597372.47      6970240.29      1597237.06      6969706.46
      1597000.09      6969143.98
#Sta/Elev= 30
  4448.4 1584.39  4498.2 1582.25  4595.2 1578.90  4708.7 1576.46  4791.2 1575.76
  4925.3 1575.99  4976.9 1575.10  5015.5 1573.58  5062.6 1574.00  5068.4 1574.54
  5073.8 1574.22  5092.1 1574.33  5103.2 1573.51  5103.7 1573.01  5108.3 1573.01
  5108.7 1573.51  5117.8 1575.10  5121.3 1575.99  5127.7 1576.19  5138.5 1574.81
  5149.9 1575.41  5192.5 1575.41  5257.9 1576.69  5344.7 1577.41  5409.8 1579.07
  5464.1 1579.90  5518.3 1580.10  5540.0 1579.79  5550.9 1579.19  5609.5 1580.81
#Mann=5,-1,0
  4448.4   0.045       0  5103.2   0.045       0  5108.7   0.045       0
  5117.8    0.07       0  5149.9   0.045       0
Bank Sta=5103.2,5108.7
Exp/Cntr=0.3,0.1

Type RM Length L Ch R = 1,3936,649,649,649
BEGIN DESCRIPTION:
Mapping XS 633ae949
END DESCRIPTION:
XS GIS Cut Line= 4
      1597480.91      6970235.99      1597546.88      6969291.57
      1597530.39      6968714.41      1596934.84      6968219.76
#Sta/Elev= 30
  4057.9 1585.56  4116.0 1584.38  4156.1 1582.55  4226.3 1580.17  4326.5 1578.23
  4376.7 1576.84  4615.6 1574.29  4802.9 1573.63  4958.1 1573.24  4978.1 1573.74
  5008.9 1572.91  5025.5 1570.29  5025.9 1569.79  5030.5 1569.79  5031.0 1570.29
  5038.2 1570.59  5048.2 1572.11  5118.2 1571.57  5153.9 1571.69  5188.3 1571.45
  5318.3 1571.76  5348.3 1572.78  5388.4 1573.35  5589.9 1573.48  5618.5 1573.75
  5661.5 1574.99  5760.5 1575.38  5817.8 1576.66  6287.2 1576.90  6356.2 1576.59
#Mann=6,-1,0
  4057.9   0.045       0  4802.9    0.07       0  5025.5    0.07       0
  5031.0    0.07       0  5153.9   0.045       0  6287.2   0.035       0
Bank Sta=5025.5,5031
Exp/Cntr=0.3,0.1

Type RM Length L Ch R = 1,3287,1112,1112,1112
BEGIN DESCRIPTION:
Mapping XS 4263d09a
END DESCRIPTION:
XS GIS Cut Line= 3
      1598074.66      6970225.62      1598067.71      6969024.21
      1596750.09      6967619.91
#Sta/Elev= 30
  3800.4 1584.31  4118.0 1582.16  4418.0 1577.78  4628.0 1571.79  4873.2 1569.20
  4985.8 1566.89  5012.3 1566.74  5012.8 1566.24  5018.0 1566.74  5018.4 1566.76
  5057.6 1568.61  5073.6 1568.16  5128.5 1567.87  5206.1 1569.78  5475.2 1569.92
  5581.3 1571.03  5630.6 1572.83  5836.1 1573.40  5875.3 1573.41  5970.2 1573.03
  6005.7 1574.11  6048.2 1572.67  6080.9 1572.89  6142.8 1573.40  6218.6 1573.42
  6437.0 1573.39  6495.7 1572.03  6571.8 1570.34  6670.5 1572.99  6927.5 1576.62
#Mann=13,-1,0
  3800.4   0.045       0  4873.2    0.07       0  4985.8   0.045       0
  5012.3   0.045       0  5018.0   0.045       0  5018.4    0.07       0
  5073.6   0.045       0  5836.1   0.035       0  5875.3   0.045       0
  6080.9    0.07       0  6142.8   0.035       0  6218.6   0.045       0
  6495.7   0.035       0
Bank Sta=5012.3,5018
Exp/Cntr=0.3,0.1

Type RM Length L Ch R = 1,2175,1832,1832,1832
BEGIN DESCRIPTION:
Mapping XS b76ceca0
END DESCRIPTION:
XS GIS Cut Line= 3
      1598652.55      6969135.18      1598544.92      6968097.84
      1596979.99      6967563.00
#Sta/Elev= 30
  3957.1 1574.70  4195.5 1572.83  4306.1 1573.06  4607.7 1565.74  4688.2 1565.02
  4854.0 1566.14  4939.5 1564.31  4969.7 1564.66  5015.4 1563.92  5038.5 1563.06
  5039.0 1562.56  5043.8 1562.56  5044.3 1563.06  5052.8 1563.94  5078.0 1563.75
  5109.3 1564.74  5158.4 1564.39  5803.1 1566.59  5944.2 1567.53  5970.2 1568.31
  6056.7 1567.74  6095.9 1568.22  6139.0 1568.51  6439.9 1570.53  6465.9 1571.92
  6490.0 1572.16  6511.1 1573.14  6553.4 1573.26  6627.8 1575.22  6653.8 1575.13
#Mann=5,-1,0
  3957.1   0.045       0  5038.5   0.045       0  5044.3   0.045       0
  6095.9    0.07       0  6139.0   0.045       0
Bank Sta=5038.5,5044.3
Exp/Cntr=0.3,0.1

Type RM Length L Ch R = 1,343,0,0,0
BEGIN DESCRIPTION:
Mapping XS 614313f2
END DESCRIPTION:
XS GIS Cut Line= 3
      1600222.19      6968877.65      1600174.98      6967867.96
      1596893.21      6967348.71
#Sta/Elev= 30
  3989.2 1567.37  4247.2 1562.21  4509.4 1560.17  4893.7 1561.28  5028.5 1557.65
  5435.3 1562.21  5526.5 1558.66  5542.6 1560.91  5617.6 1562.98  5864.6 1563.46
  6022.5 1561.05  6194.7 1562.31  6214.9 1563.26  6243.9 1569.71  6255.4 1570.59
  6275.7 1568.27  6311.3 1557.56  6322.1 1556.99  6322.6 1556.49  6330.5 1556.99
  6417.4 1557.23  6447.8 1563.64  6633.3 1562.63  6994.5 1566.24  7401.9 1565.00
  7629.0 1567.40  7787.9 1568.14  8047.4 1569.99  8191.8 1573.82  8322.6 1576.74
#Mann=6,-1,0
  3989.2   0.045       0  6322.1   0.045       0  6330.5   0.045       0
  7629.0    0.07       0  7787.9   0.045       0  8191.8   0.035       0
Bank Sta=6322.1,6330.5
Exp/Cntr=0.3,0.1

Chan Stop Cuts=-1