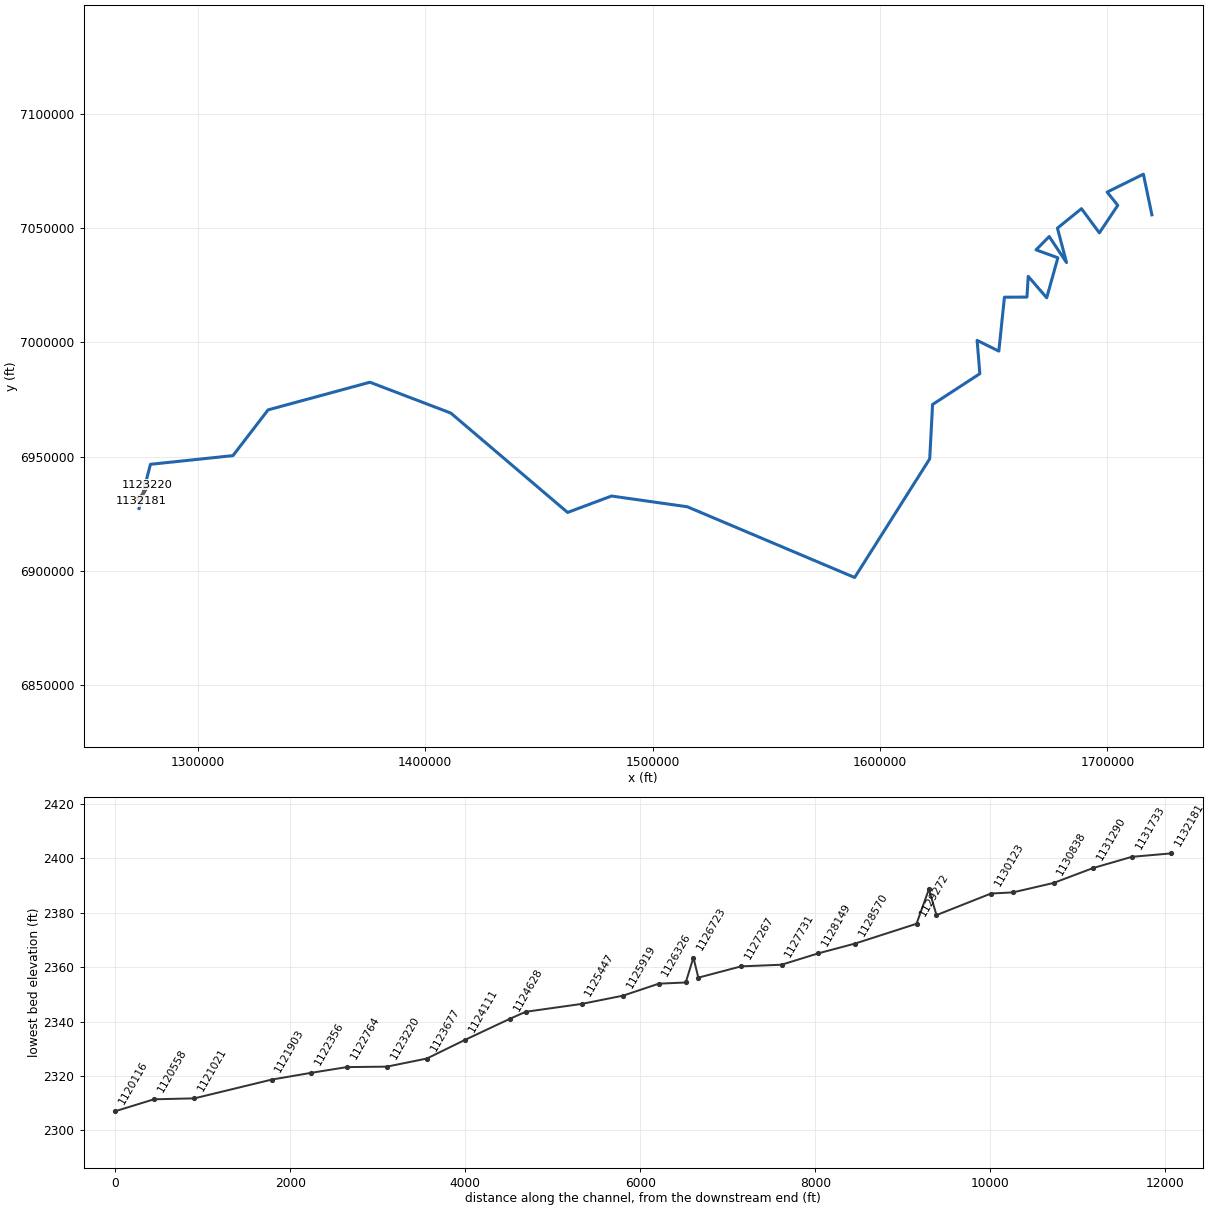
--- Clear Fork Brazos Rv.prj (project) ---

Proj Title=Clear Fork Brazos Rv Base Level Engineering
Current Plan=p01
Default Exp/Contr=0.3,0.1
English Units
Geom File=g01
Flow File=f01
Plan File=p01
Y Axis Title=Elevation
X Axis Title(PF)=Main Channel Distance
X Axis Title(XS)=Station
BEGIN DESCRIPTION:
Clear Fork Brazos Rv
END DESCRIPTION:
DSS Export Rating Curves= 0
DSS Export Rating Curve Sorted= 0
DSS Export Volume Flow Curves= 0
DXF OffsetX= 0
DXF OffsetY= 0
DXF ScaleX= 1
DXF ScaleY= 10

--- Clear Fork Brazos Rv.p01 (plan) ---

Plan Title=Multiple Run
Short Identifier=Multiple
Geom File=g01
Flow File=f01
Subcritical Flow
K Sum by GR= 0
Std Step Tol= 0.01
Critical Tol= 0.01
Num of Std Step Trials= 20
Max Error Tol= 0.3
Flow Tol Ratio= 0.001
Split Flow NTrial= 30
Split Flow Tol= 0.02
Split Flow Ratio= 0.02
Log Output Level= 0
Friction Slope Method= 1
Unsteady Friction Slope Method= 2
Unsteady Bridges Friction Slope Method= 1
Parabolic Critical Depth
Global Vel Dist=  1 , 1 , 1
Global Log Level= 0
CheckData=True
Encroach Param= -1, 0, 0, 0
BEGIN DESCRIPTION:
Multiple Run
END DESCRIPTION:

--- Clear Fork Brazos Rv.f01 (steady flow) ---

Flow Title=Multiple
Number of Profiles=7
Profile Names=10-year,25-year,50-year,1pct_min,100-year,1pct_plu,500-year
River Rch & RM= Clear Fork Brazo,Reach-1,1132181
     162     216     260     193     309     425     442
River Rch & RM= Clear Fork Brazo,Reach-1,1131290
     403     577     723     560     898    1240    1400
River Rch & RM= Clear Fork Brazo,Reach-1,1123677
     606     887    1130     889    1420    1960    2290
River Rch & RM= Clear Fork Brazo,Reach-1,1120558
    1130    1700    2200    1760    2820    3890    4700
River Rch & RM= Clear Fork Brazo,Reach-1,1113588
    1490    2260    2950    2370    3810    5240    6400
River Rch & RM= Clear Fork Brazo,Reach-1,1109481
    1520    2310    3020    2420    3890    5350    6530
River Rch & RM= Clear Fork Brazo,Reach-1,1104994
    1730    2630    3440    2770    4440    6110    7490
River Rch & RM= Clear Fork Brazo,Reach-1,1098384
    1820    2770    3630    2920    4680    6440    7910
River Rch & RM= Clear Fork Brazo,Reach-1,1096148
    1990    3050    4000    3230    5180    7130    8790
River Rch & RM= Clear Fork Brazo,Reach-1,1085195
    2240    3450    4530    3670    5880    8090   10000
River Rch & RM= Clear Fork Brazo,Reach-1,1075046
    2590    4000    5280    4280    6860    9440   11800
River Rch & RM= Clear Fork Brazo,Reach-1,1072004
    2650    4090    5390    4370    7000    9640   12000
River Rch & RM= Clear Fork Brazo,Reach-1,1066390
    2780    4290    5660    4590    7350   10100   12600
River Rch & RM= Clear Fork Brazo,Reach-1,1058773
    2750    4230    5570    4500    7210    9930   12300
River Rch & RM= Clear Fork Brazo,Reach-1,1050520
    2860    4370    5730    4620    7410   10200   12500
River Rch & RM= Clear Fork Brazo,Reach-1,1031513
    3190    4890    6430    5190    8320   11400   14100
River Rch & RM= Clear Fork Brazo,Reach-1,1026656
    3330    5090    6690    5400    8650   11900   14600
River Rch & RM= Clear Fork Brazo,Reach-1,1011603
    4260    7760   11300    9950   15900   21900   32900
River Rch & RM= Clear Fork Brazo,Reach-1,999476
    4500    8110   11700   10200   16400   22600   33200
River Rch & RM= Clear Fork Brazo,Reach-1,990232
    4560    8200   11800   10300   16500   22700   33300
River Rch & RM= Clear Fork Brazo,Reach-1,976205
    4670    8350   12000   10400   16700   23000   33400
River Rch & RM= Clear Fork Brazo,Reach-1,937632
    4920    8720   12400   10700   17200   23700   33700
River Rch & RM= Clear Fork Brazo,Reach-1,918109
    5160    9070   12800   11000   17700   24300   34000
River Rch & RM= Clear Fork Brazo,Reach-1,900419
    6200   10500   14500   12200   19500   26800   35000
River Rch & RM= Clear Fork Brazo,Reach-1,856968
    6700   11200   15300   12700   20300   28000   35400
River Rch & RM= Clear Fork Brazo,Reach-1,713969
    7560   12400   16600   13500   21700   29800   36100
River Rch & RM= Clear Fork Brazo,Reach-1,693547
    7810   12700   17000   13800   22100   30400   36300
River Rch & RM= Clear Fork Brazo,Reach-1,536172
    8030   13000   17300   14000   22400   30800   36500
River Rch & RM= Clear Fork Brazo,Reach-1,535538
    8450   13500   17900   14400   23000   31700   36800
River Rch & RM= Clear Fork Brazo,Reach-1,432176
    9090   14400   18800   14900   23900   32900   37200
River Rch & RM= Clear Fork Brazo,Reach-1,419211
    9260   14600   19100   15100   24200   33300   37400
River Rch & RM= Clear Fork Brazo,Reach-1,389993
    9390   14800   19200   15200   24400   33500   37400
River Rch & RM= Clear Fork Brazo,Reach-1,318213
    9610   15000   19500   15400   24700   33900   37600
Boundary for River Rch & Prof#=Clear Fork Brazo,Reach-1,1
Up Type=0
Dn Type=3
Dn Slope=0.0005
Boundary for River Rch & Prof#=Clear Fork Brazo,Reach-1,2
Up Type=0
Dn Type=3
Dn Slope=0.0005
Boundary for River Rch & Prof#=Clear Fork Brazo,Reach-1,3
Up Type=0
Dn Type=3
Dn Slope=0.0005
Boundary for River Rch & Prof#=Clear Fork Brazo,Reach-1,4
Up Type=0
Dn Type=3
Dn Slope=0.0005
Boundary for River Rch & Prof#=Clear Fork Brazo,Reach-1,5
Up Type=0
Dn Type=3
Dn Slope=0.0005
Boundary for River Rch & Prof#=Clear Fork Brazo,Reach-1,6
Up Type=0
Dn Type=3
Dn Slope=0.0005
Boundary for River Rch & Prof#=Clear Fork Brazo,Reach-1,7
Up Type=0
Dn Type=3
Dn Slope=0.0005

--- Clear Fork Brazos Rv.g01 (geometry) ---

Geom Title=Existing Conditions

River Reach=Clear Fork Brazo,Reach-1
Reach XY= 30
      1274155.00      6927238.00      1279163.17      6946585.55
      1315453.42      6950391.82      1330902.55      6970432.54
      1375689.63      6982538.11      1411261.19      6969030.25
      1462606.50      6925491.46      1481929.92      6932688.20
      1515244.50      6927986.80      1588849.06      6896990.26
      1621851.17      6948989.58      1623113.16      6972794.05
      1643896.86      6986281.94      1642695.32      7000877.24
      1652249.17      6996185.70      1654712.48      7019794.06
      1664618.30      7019851.40      1665170.18      7028938.43
      1673299.17      7019535.70      1678204.35      7037072.16
      1668618.63      7040551.21      1674403.42      7046384.33
      1682011.17      7034995.86      1678021.65      7050054.67
      1688589.78      7058587.48      1696457.45      7047993.45
      1704553.78      7060048.50      1699865.48      7065847.80
      1715815.50      7073686.81      1719555.00      7055888.00

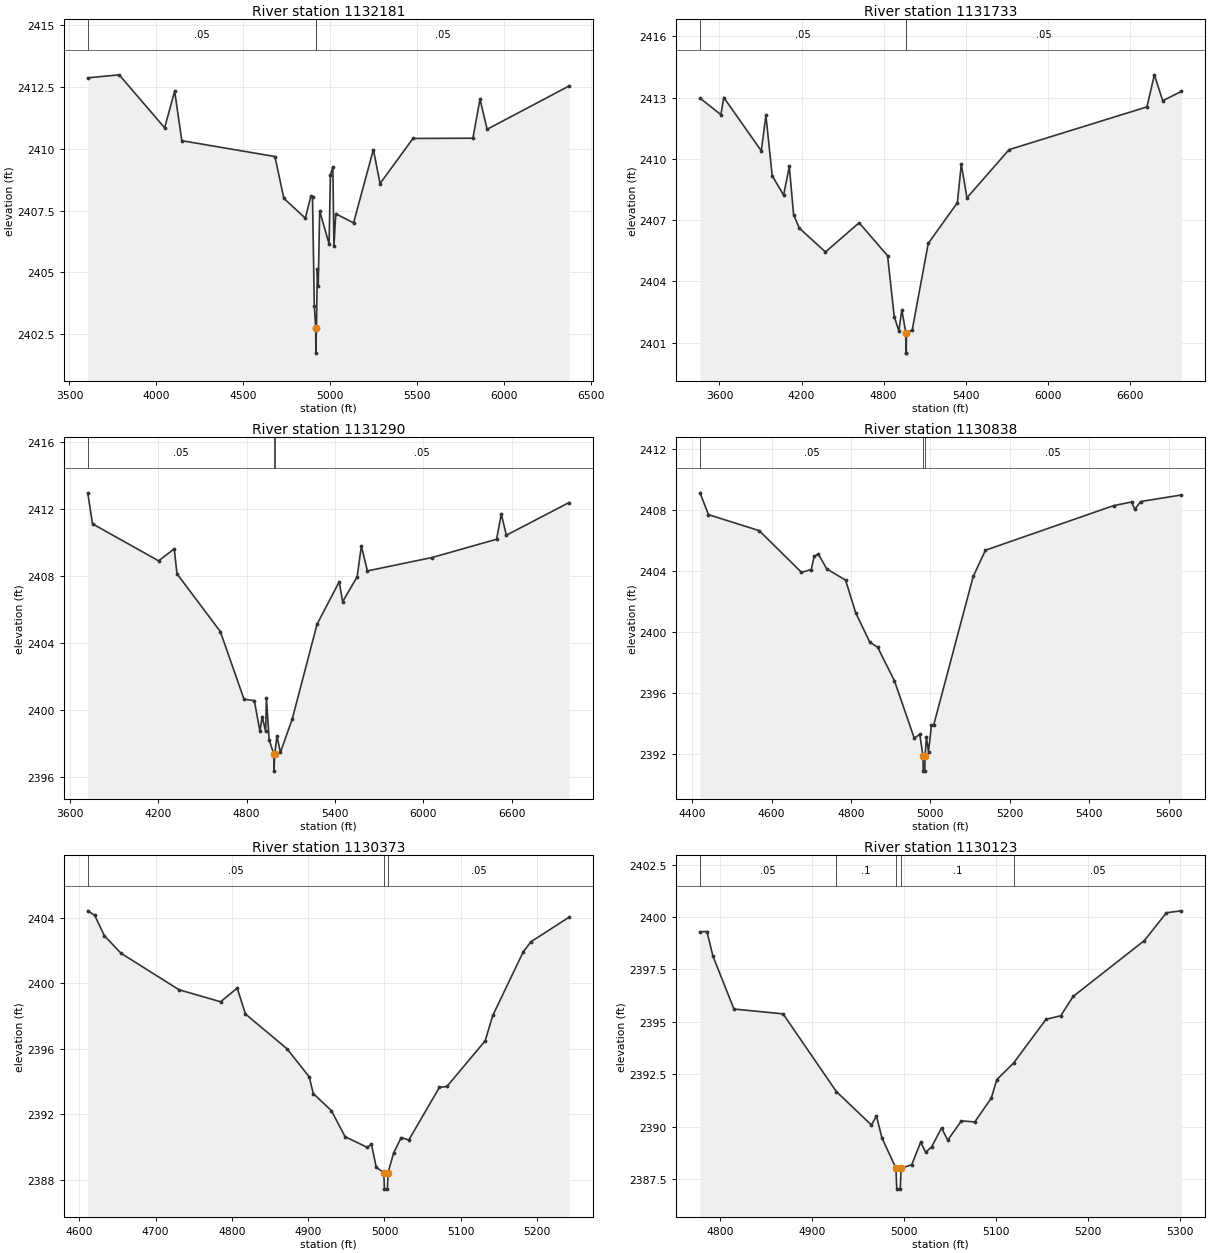
Type RM Length L Ch R = 1,1132181,448,448,448
BEGIN DESCRIPTION:
Clear Fork Brazos Rv 439.0
END DESCRIPTION:
XS GIS Cut Line= 3
      1272259.40      6930457.86      1273605.00      6930788.00
      1274954.96      6930488.01
#Sta/Elev= 30
  3605.3 2412.86  3786.1 2412.98  4047.6 2410.84  4105.3 2412.32  4146.5 2410.32
  4681.9 2409.68  4733.4 2407.99  4856.9 2407.19  4889.4 2408.10  4898.1 2408.03
  4908.4 2403.66  4916.7 2402.74  4917.2 2401.74  4920.7 2402.74  4925.9 2405.15
  4931.0 2404.46  4939.3 2407.48  4993.4 2406.15  5001.0 2408.92  5015.1 2409.27
  5021.5 2406.06  5031.8 2407.37  5134.2 2407.00  5248.2 2409.96  5286.6 2408.59
  5476.1 2410.41  5820.6 2410.42  5861.5 2412.00  5902.5 2410.78  6373.7 2412.53
#Mann=3,-1,0
  3605.3    0.05       0  4916.7    0.05       0  4920.7    0.05       0
Bank Sta=4916.7,4920.7
Exp/Cntr=0.3,0.1

Type RM Length L Ch R = 1,1131733,443,443,443
BEGIN DESCRIPTION:
Clear Fork Brazos Rv 438.0
END DESCRIPTION:
XS GIS Cut Line= 3
      1272118.07      6930759.54      1273605.00      6931188.00
      1275404.99      6930388.00
#Sta/Elev= 30
  3458.2 2412.97  3610.5 2412.16  3631.9 2413.00  3905.9 2410.39  3939.6 2412.12
  3985.8 2409.17  4069.0 2408.22  4110.6 2409.63  4141.9 2407.27  4183.5 2406.61
  4374.8 2405.44  4620.6 2406.87  4828.7 2405.26  4877.4 2402.28  4911.1 2401.58
  4932.8 2402.61  4961.9 2401.49  4962.5 2400.49  4965.6 2400.49  4966.1 2401.49
  5008.4 2401.61  5126.0 2405.86  5338.7 2407.85  5367.4 2409.74  5408.5 2408.09
  5716.9 2410.45  6723.7 2412.54  6778.4 2414.11  6839.3 2412.84  6975.4 2413.30
#Mann=3,-1,0
  3458.2    0.05       0  4961.9    0.03       0  4966.1    0.05       0
Bank Sta=4961.9,4966.1
Exp/Cntr=0.3,0.1

Type RM Length L Ch R = 1,1131290,452,452,452
BEGIN DESCRIPTION:
Clear Fork Brazos Rv 437.0
END DESCRIPTION:
XS GIS Cut Line= 3
      1272304.97      6932088.01      1273505.00      6931588.00
      1275304.99      6930788.00
#Sta/Elev= 30
  3720.7 2412.98  3753.2 2411.13  4202.3 2408.92  4308.4 2409.64  4326.9 2408.15
  4621.5 2404.70  4782.4 2400.66  4852.3 2400.58  4890.7 2398.75  4905.4 2399.63
  4929.2 2398.74  4934.6 2400.73  4953.0 2398.25  4985.5 2397.37  4986.4 2396.37
  4990.9 2397.37  5006.1 2398.47  5029.6 2397.49  5110.3 2399.49  5278.6 2405.14
  5429.1 2407.67  5452.3 2406.48  5550.8 2407.97  5579.5 2409.80  5620.6 2408.32
  6060.3 2409.12  6498.1 2410.21  6530.2 2411.72  6564.4 2410.45  6990.5 2412.40
#Mann=3,-1,0
  3720.7    0.05       0  4985.5    0.05       0  4990.9    0.05       0
Bank Sta=4985.5,4990.9
Exp/Cntr=0.3,0.1

Type RM Length L Ch R = 1,1130838,465,465,465
BEGIN DESCRIPTION:
Clear Fork Brazos Rv 436.0
END DESCRIPTION:
XS GIS Cut Line= 3
      1273055.01      6932188.00      1273605.00      6931988.00
      1274154.98      6931688.01
#Sta/Elev= 30
  4420.0 2409.13  4441.3 2407.70  4569.0 2406.65  4675.4 2403.92  4700.0 2404.10
  4707.3 2404.98  4717.9 2405.11  4739.2 2404.14  4786.4 2403.41  4811.7 2401.28
  4847.6 2399.33  4866.9 2399.02  4909.5 2396.81  4959.3 2393.05  4973.3 2393.30
  4981.2 2391.89  4982.1 2390.89  4985.8 2390.89  4986.7 2391.89  4989.9 2393.12
  4995.2 2392.16  5002.6 2393.90  5008.1 2393.90  5107.7 2403.65  5138.6 2405.37
  5460.9 2408.29  5506.4 2408.53  5514.5 2408.04  5529.2 2408.56  5631.7 2408.99
#Mann=3,-1,0
  4420.0    0.05       0  4981.2    0.05       0  4986.7    0.05       0
Bank Sta=4981.2,4986.7
Exp/Cntr=0.3,0.1

Type RM Length L Ch R = 1,1130373,250,250,250
BEGIN DESCRIPTION:
Clear Fork Brazos Rv 435.0
END DESCRIPTION:
XS GIS Cut Line= 3
      1273754.99      6932688.03      1273905.00      6932338.00
      1273905.00      6932088.02
#Sta/Elev= 30
  4611.1 2404.41  4620.2 2404.14  4632.9 2402.89  4654.7 2401.82  4730.8 2399.59
  4785.2 2398.86  4807.0 2399.69  4817.8 2398.11  4872.2 2395.99  4901.3 2394.28
  4906.7 2393.25  4930.3 2392.22  4948.4 2390.62  4977.4 2389.97  4982.9 2390.16
  4989.2 2388.76  4999.1 2388.42  5000.0 2387.42  5003.8 2387.42  5004.7 2388.42
  5011.9 2389.62  5021.9 2390.57  5031.9 2390.42  5071.9 2393.63  5081.9 2393.69
  5131.9 2396.47  5141.9 2398.02  5181.9 2401.91  5191.9 2402.52  5241.9 2404.02
#Mann=3,-1,0
  4611.1    0.05       0  4999.1    0.05       0  5004.7    0.05       0
Bank Sta=4999.1,5004.7
Exp/Cntr=0.3,0.1

Type RM Length L Ch R = 1,1130123,623,623,623
BEGIN DESCRIPTION:
Mapping XS c34b8440
END DESCRIPTION:
XS GIS Cut Line= 2
      1274017.64      6932641.05      1274215.57      6932156.63
#Sta/Elev= 30
  4777.8 2399.30  4785.3 2399.31  4791.9 2398.13  4814.7 2395.61  4868.1 2395.38
  4926.0 2391.67  4964.2 2390.07  4969.6 2390.51  4975.5 2389.47  4990.8 2388.01
  4991.7 2387.01  4995.5 2387.01  4996.4 2388.01  5007.9 2388.17  5017.7 2389.25
  5023.1 2388.77  5029.6 2389.03  5040.4 2389.93  5047.1 2389.35  5062.0 2390.27
  5076.5 2390.22  5094.4 2391.35  5100.5 2392.24  5118.7 2393.03  5154.0 2395.12
  5170.0 2395.29  5183.4 2396.21  5260.9 2398.88  5284.9 2400.21  5301.1 2400.30
#Mann=5,-1,0
  4777.8    0.05       0  4926.0     0.1       0  4990.8    0.07       0
  4996.4     0.1       0  5118.7    0.05       0
Bank Sta=4990.8,4996.4
Exp/Cntr=0.3,0.1

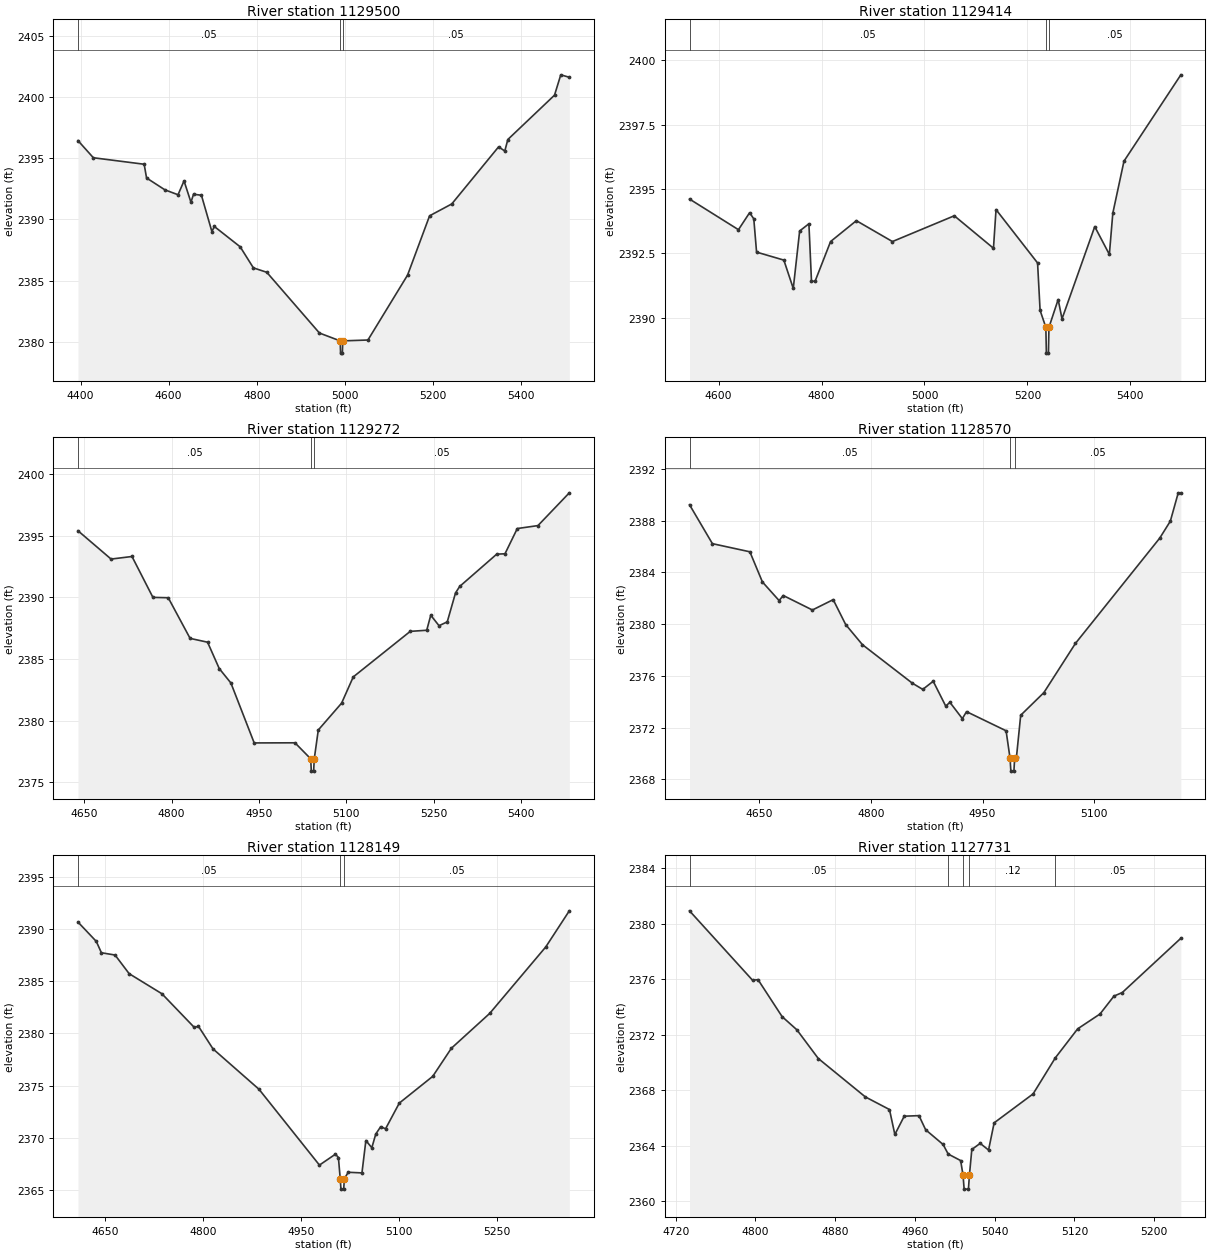
Type RM Length L Ch R = 1,1129500,86,86,86
BEGIN DESCRIPTION:
Mapping XS f43ddbc4
END DESCRIPTION:
XS GIS Cut Line= 4
      1274082.75      6932651.43      1274395.25      6932521.23
      1274897.86      6932531.64      1275087.97      6932333.71
#Sta/Elev= 30
  4394.2 2396.43  4429.1 2395.03  4544.5 2394.50  4549.9 2393.38  4591.6 2392.41
  4621.4 2392.01  4635.0 2393.14  4650.7 2391.40  4656.6 2392.05  4674.5 2391.97
  4698.3 2389.00  4703.8 2389.42  4762.5 2387.76  4792.5 2386.04  4822.9 2385.68
  4942.5 2380.72  4989.5 2380.08  4990.5 2379.08  4994.5 2379.08  4995.5 2380.08
  5052.6 2380.15  5142.6 2385.45  5192.6 2390.29  5243.0 2391.26  5349.3 2395.92
  5363.4 2395.58  5370.3 2396.52  5476.3 2400.14  5490.5 2401.80  5509.9 2401.60
#Mann=3,-1,0
  4394.2    0.05       0  4989.5    0.05       0  4995.5    0.05       0
Bank Sta=4989.5,4995.5
Exp/Cntr=0.3,0.1

Type RM Length L Ch R = 1,1129414,142,142,142
BEGIN DESCRIPTION:
Mapping XS 01a964e9
END DESCRIPTION:
XS GIS Cut Line= 4
      1274257.25      6932672.26      1274449.94      6932591.54
      1274913.48      6932617.58      1275100.51      6932407.18
#Sta/Elev= 30
  4543.5 2394.61  4638.6 2393.42  4660.3 2394.08  4668.4 2393.84  4673.8 2392.55
  4726.8 2392.24  4745.1 2391.14  4757.5 2393.37  4775.5 2393.65  4780.5 2391.42
  4787.5 2391.42  4817.6 2392.96  4867.7 2393.77  4937.8 2392.96  5058.0 2393.96
  5134.1 2392.70  5139.1 2394.20  5219.8 2392.13  5224.7 2390.29  5235.9 2389.63
  5236.9 2388.63  5240.9 2388.63  5241.9 2389.63  5259.8 2390.71  5267.3 2389.96
  5330.9 2393.54  5359.3 2392.46  5366.0 2394.06  5387.7 2396.08  5498.2 2399.43
#Mann=3,-1,0
  4543.5    0.05       0  5235.9    0.05       0  5241.9    0.05       0
Bank Sta=5235.9,5241.9
Exp/Cntr=0.3,0.1

Type RM Length L Ch R = 1,1129272,702,702,702
BEGIN DESCRIPTION:
Mapping XS 76f9e8a6
END DESCRIPTION:
XS GIS Cut Line= 4
      1274447.36      6932797.26      1274574.94      6932713.93
      1274942.13      6932716.54      1275165.71      6932482.56
#Sta/Elev= 30
  4639.3 2395.42  4696.1 2393.12  4732.0 2393.33  4767.9 2390.01  4794.2 2389.98
  4831.7 2386.68  4861.7 2386.37  4881.7 2384.23  4901.7 2383.06  4941.7 2378.19
  5011.7 2378.20  5038.7 2376.90  5039.7 2375.90  5043.7 2375.90  5044.8 2376.90
  5051.7 2379.24  5091.7 2381.42  5111.7 2383.55  5209.5 2387.25  5237.8 2387.34
  5244.7 2388.56  5258.9 2387.71  5273.0 2388.02  5287.2 2390.37  5294.4 2390.90
  5357.9 2393.52  5372.1 2393.55  5393.2 2395.60  5428.7 2395.84  5482.5 2398.50
#Mann=3,-1,0
  4639.3    0.05       0  5038.7    0.05       0  5044.8    0.05       0
Bank Sta=5038.7,5044.8
Exp/Cntr=0.3,0.1

Type RM Length L Ch R = 1,1128570,421,421,421
BEGIN DESCRIPTION:
Clear Fork Brazos Rv 431.0
END DESCRIPTION:
XS GIS Cut Line= 3
      1274955.02      6933287.99      1275355.00      6933088.00
      1275504.99      6932938.01
#Sta/Elev= 30
  4556.7 2389.24  4587.4 2386.23  4637.7 2385.60  4654.5 2383.27  4676.9 2381.83
  4682.5 2382.22  4721.6 2381.10  4749.5 2381.90  4766.3 2379.97  4788.7 2378.42
  4855.7 2375.44  4869.7 2374.96  4883.7 2375.59  4900.5 2373.67  4906.1 2373.96
  4922.8 2372.70  4928.4 2373.24  4981.5 2371.76  4986.8 2369.64  4987.9 2368.64
  4992.0 2368.64  4993.0 2369.64  4995.5 2369.77  5001.1 2372.96  5032.2 2374.71
  5074.6 2378.52  5187.7 2386.66  5201.9 2387.97  5212.5 2390.16  5216.0 2390.16
#Mann=3,-1,0
  4556.7    0.05       0  4986.8    0.05       0  4993.0    0.05       0
Bank Sta=4986.8,4993
Exp/Cntr=0.3,0.1

Type RM Length L Ch R = 1,1128149,418,418,418
BEGIN DESCRIPTION:
Clear Fork Brazos Rv 430.0
END DESCRIPTION:
XS GIS Cut Line= 3
      1275354.97      6933688.04      1275605.00      6933388.00
      1275804.99      6933088.01
#Sta/Elev= 30
  4609.0 2390.71  4637.0 2388.85  4644.8 2387.76  4665.7 2387.54  4687.2 2385.75
  4737.3 2383.82  4786.7 2380.59  4793.2 2380.69  4815.4 2378.52  4885.7 2374.64
  4978.1 2367.35  5002.6 2368.40  5007.1 2368.08  5009.9 2366.04  5011.0 2365.04
  5015.2 2365.04  5016.2 2366.04  5022.1 2366.66  5043.1 2366.60  5049.1 2369.71
  5058.2 2369.02  5064.2 2370.33  5071.7 2371.04  5079.2 2370.84  5100.2 2373.31
  5151.3 2375.88  5179.8 2378.58  5238.4 2381.93  5324.1 2388.32  5360.1 2391.79
#Mann=3,-1,0
  4609.0    0.05       0  5009.9    0.05       0  5016.2    0.05       0
Bank Sta=5009.9,5016.2
Exp/Cntr=0.3,0.1

Type RM Length L Ch R = 1,1127731,464,464,464
BEGIN DESCRIPTION:
Clear Fork Brazos Rv 429.0
END DESCRIPTION:
XS GIS Cut Line= 3
      1275805.00      6933887.99      1275905.00      6933638.00
      1276005.02      6933437.96
#Sta/Elev= 30
  4733.9 2380.94  4797.2 2375.93  4802.6 2375.98  4826.8 2373.31  4841.6 2372.36
  4863.1 2370.29  4910.3 2367.52  4934.5 2366.61  4939.9 2364.81  4949.3 2366.13
  4964.1 2366.17  4970.8 2365.15  4988.3 2364.09  4993.4 2363.40  5005.9 2362.93
  5008.3 2361.87  5009.4 2360.87  5013.7 2360.87  5014.7 2361.87  5017.1 2363.73
  5025.5 2364.17  5033.9 2363.69  5039.5 2365.65  5078.6 2367.74  5100.9 2370.34
  5123.3 2372.43  5145.7 2373.50  5159.7 2374.79  5168.1 2375.05  5226.8 2378.96
#Mann=5,-1,0
  4733.9    0.05       0  4993.4    0.12       0  5008.3    0.07       0
  5014.7    0.12       0  5100.9    0.05       0
Bank Sta=5008.3,5014.7
Exp/Cntr=0.3,0.1

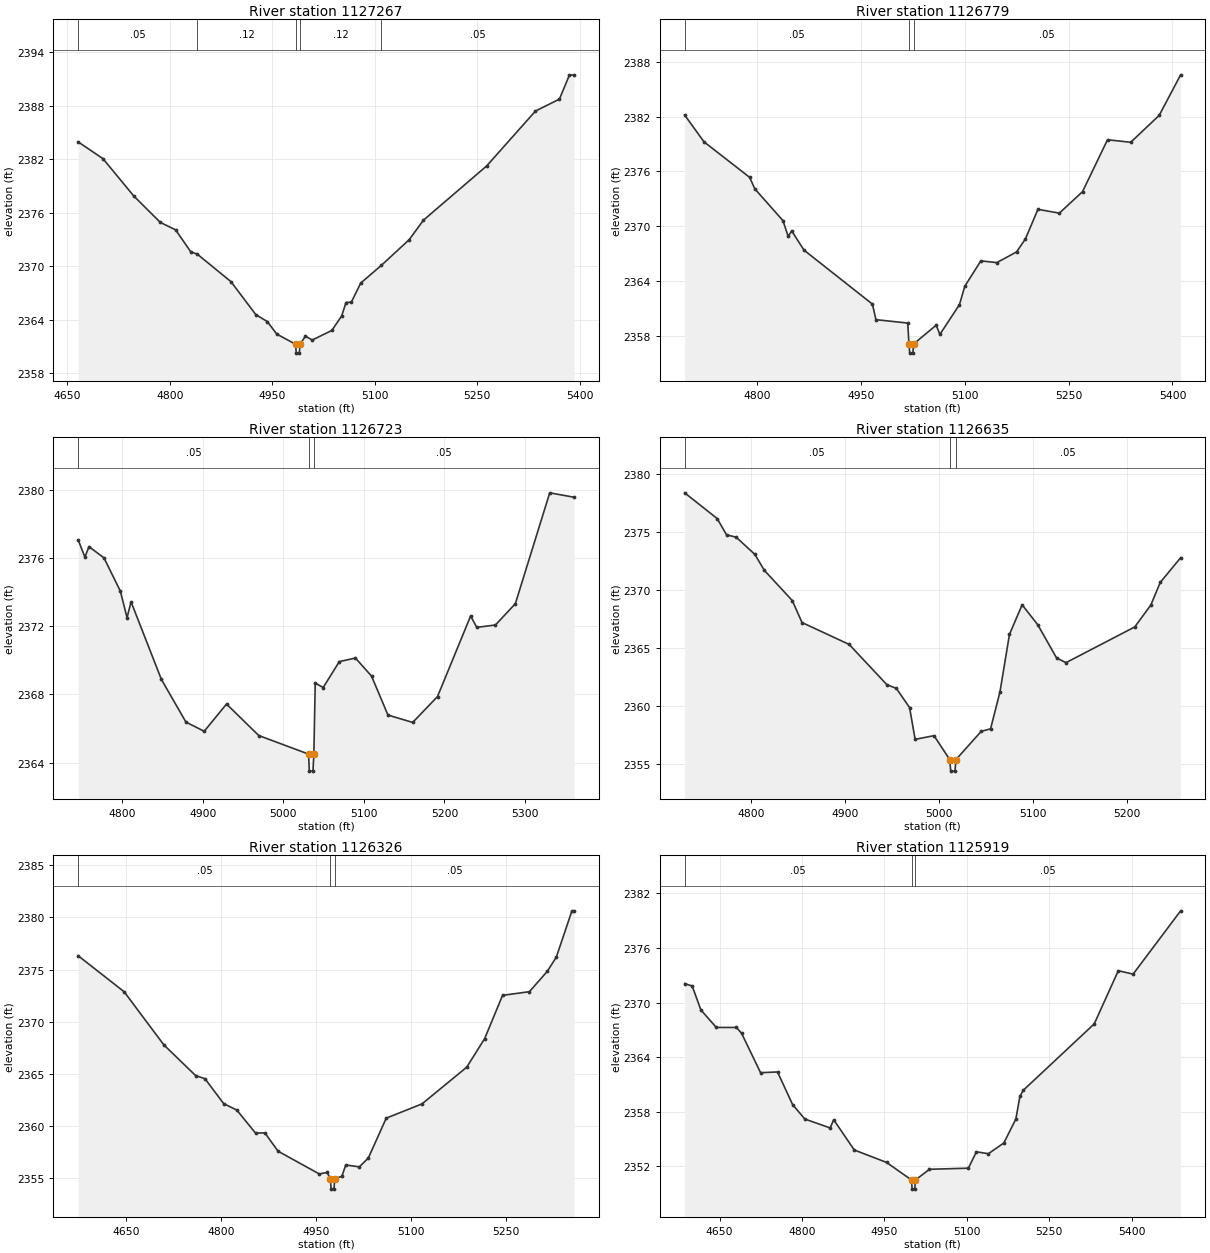
Type RM Length L Ch R = 1,1127267,488,488,488
BEGIN DESCRIPTION:
Clear Fork Brazos Rv 428.0
END DESCRIPTION:
XS GIS Cut Line= 3
      1275955.00      6934038.00      1276255.00      6933888.00
      1276554.99      6933638.01
#Sta/Elev= 30
  4666.0 2383.93  4702.3 2382.05  4747.1 2377.89  4786.2 2374.91  4808.5 2374.08
  4830.9 2371.60  4840.2 2371.36  4889.6 2368.27  4925.9 2364.58  4942.7 2363.80
  4956.7 2362.39  4984.1 2361.26  4985.2 2360.26  4989.6 2360.26  4990.7 2361.26
  4998.6 2362.16  5008.6 2361.73  5037.2 2362.80  5051.5 2364.41  5058.0 2365.93
  5065.8 2365.98  5079.5 2368.11  5109.9 2370.11  5150.5 2372.98  5171.3 2375.16
  5263.7 2381.23  5335.3 2387.39  5370.4 2388.73  5384.8 2391.40  5391.9 2391.45
#Mann=5,-1,0
  4666.0    0.05       0  4840.2    0.12       0  4984.1    0.07       0
  4990.7    0.12       0  5109.9    0.05       0
Bank Sta=4984.1,4990.7
Exp/Cntr=0.3,0.1

Type RM Length L Ch R = 1,1126779,56,56,56
BEGIN DESCRIPTION:
Clear Fork Brazos Rv 427.0
END DESCRIPTION:
XS GIS Cut Line= 3
      1276055.01      6934388.00      1276355.00      6934338.00
      1276754.96      6934238.01
#Sta/Elev= 30
  4695.4 2382.16  4723.3 2379.23  4789.2 2375.35  4796.8 2374.08  4837.3 2370.62
  4844.9 2368.89  4850.0 2369.49  4867.7 2367.39  4966.6 2361.48  4971.7 2359.78
  5017.6 2359.41  5019.4 2357.12  5020.5 2356.12  5025.0 2356.12  5026.0 2357.12
  5058.8 2359.18  5064.0 2358.16  5092.3 2361.42  5100.0 2363.43  5123.2 2366.21
  5146.4 2366.02  5174.8 2367.19  5187.6 2368.61  5205.7 2371.85  5236.6 2371.43
  5270.1 2373.78  5306.2 2379.46  5339.7 2379.18  5380.9 2382.13  5411.8 2386.56
#Mann=3,-1,0
  4695.4    0.05       0  5019.4    0.03       0  5026.0    0.05       0
Bank Sta=5019.4,5026
Exp/Cntr=0.3,0.1

Type RM Length L Ch R = 1,1126723,88,88,88
BEGIN DESCRIPTION:
Mapping XS 9d4edc39
END DESCRIPTION:
XS GIS Cut Line= 4
      1276103.60      6934424.87      1276254.63      6934396.23
      1276473.38      6934391.02      1276710.22      6934336.36
#Sta/Elev= 30
  4745.4 2377.07  4753.7 2376.07  4758.8 2376.68  4777.4 2376.02  4797.7 2374.07
  4806.0 2372.51  4811.0 2373.44  4848.6 2368.89  4879.1 2366.38  4901.8 2365.84
  4929.5 2367.44  4969.5 2365.59  5031.3 2364.50  5032.3 2363.50  5036.8 2363.50
  5037.9 2364.50  5039.6 2368.67  5049.5 2368.41  5069.5 2369.93  5089.5 2370.14
  5109.5 2369.08  5129.9 2366.79  5160.6 2366.36  5191.4 2367.88  5232.5 2372.61
  5240.1 2371.94  5263.3 2372.08  5288.0 2373.33  5330.7 2379.84  5361.0 2379.58
#Mann=3,-1,0
  4745.4    0.05       0  5031.3    0.03       0  5037.9    0.05       0
Bank Sta=5031.3,5037.9
Exp/Cntr=0.3,0.1

Type RM Length L Ch R = 1,1126635,309,309,309
BEGIN DESCRIPTION:
Mapping XS de63288a
END DESCRIPTION:
XS GIS Cut Line= 2
      1276090.54      6934503.00      1276616.58      6934458.73
#Sta/Elev= 30
  4729.1 2378.36  4763.7 2376.14  4773.7 2374.73  4783.8 2374.54  4803.8 2373.05
  4813.9 2371.67  4843.6 2369.07  4854.0 2367.17  4904.2 2365.28  4944.3 2361.81
  4954.4 2361.49  4968.5 2359.83  4974.4 2357.09  4994.5 2357.41  5011.2 2355.35
  5012.3 2354.35  5016.8 2354.35  5017.9 2355.35  5044.7 2357.78  5054.7 2358.00
  5064.7 2361.18  5074.8 2366.14  5088.3 2368.70  5104.9 2366.98  5125.0 2364.11
  5135.0 2363.71  5208.2 2366.79  5225.3 2368.68  5235.3 2370.63  5257.0 2372.76
#Mann=3,-1,0
  4729.1    0.05       0  5011.2    0.03       0  5017.9    0.05       0
Bank Sta=5011.2,5017.9
Exp/Cntr=0.3,0.1

Type RM Length L Ch R = 1,1126326,407,407,407
BEGIN DESCRIPTION:
Clear Fork Brazos Rv 426.0
END DESCRIPTION:
XS GIS Cut Line= 3
      1276155.02      6934987.99      1276505.00      6934738.00
      1276754.97      6934488.03
#Sta/Elev= 30
  4574.6 2376.32  4647.1 2372.87  4709.8 2367.77  4760.1 2364.81  4774.9 2364.51
  4804.4 2362.12  4825.3 2361.49  4854.8 2359.28  4869.5 2359.31  4890.4 2357.54
  4955.5 2355.36  4967.8 2355.50  4973.1 2354.90  4974.2 2353.90  4978.7 2353.90
  4979.8 2354.90  4991.2 2355.13  4997.3 2356.22  5018.8 2356.04  5033.0 2356.89
  5061.3 2360.72  5117.8 2362.09  5188.5 2365.62  5216.8 2368.36  5245.1 2372.52
  5287.5 2372.87  5315.8 2374.83  5330.0 2376.19  5354.7 2380.64  5358.2 2380.64
#Mann=3,-1,0
  4574.6    0.05       0  4973.1    0.03       0  4979.8    0.05       0
Bank Sta=4973.1,4979.8
Exp/Cntr=0.3,0.1

Type RM Length L Ch R = 1,1125919,472,472,472
BEGIN DESCRIPTION:
Clear Fork Brazos Rv 425.0
END DESCRIPTION:
XS GIS Cut Line= 3
      1276355.02      6935287.99      1276705.00      6935088.00
      1277005.00      6934687.99
#Sta/Elev= 30
  4586.3 2372.09  4600.0 2371.82  4615.8 2369.19  4643.9 2367.27  4680.6 2367.27
  4689.9 2366.63  4724.5 2362.30  4755.4 2362.38  4782.8 2358.80  4805.1 2357.21
  4851.2 2356.23  4857.7 2357.13  4895.1 2353.81  4954.1 2352.44  4999.4 2350.51
  5000.5 2349.51  5005.3 2349.51  5006.4 2350.51  5032.1 2351.69  5102.9 2351.81
  5117.5 2353.61  5139.4 2353.40  5167.5 2354.58  5189.4 2357.21  5196.7 2359.69
  5202.9 2360.37  5332.1 2367.66  5375.9 2373.50  5402.9 2373.13  5489.4 2380.08
#Mann=3,-1,0
  4586.3    0.05       0  4999.4   0.035       0  5006.4    0.05       0
Bank Sta=4999.4,5006.4
Exp/Cntr=0.3,0.1

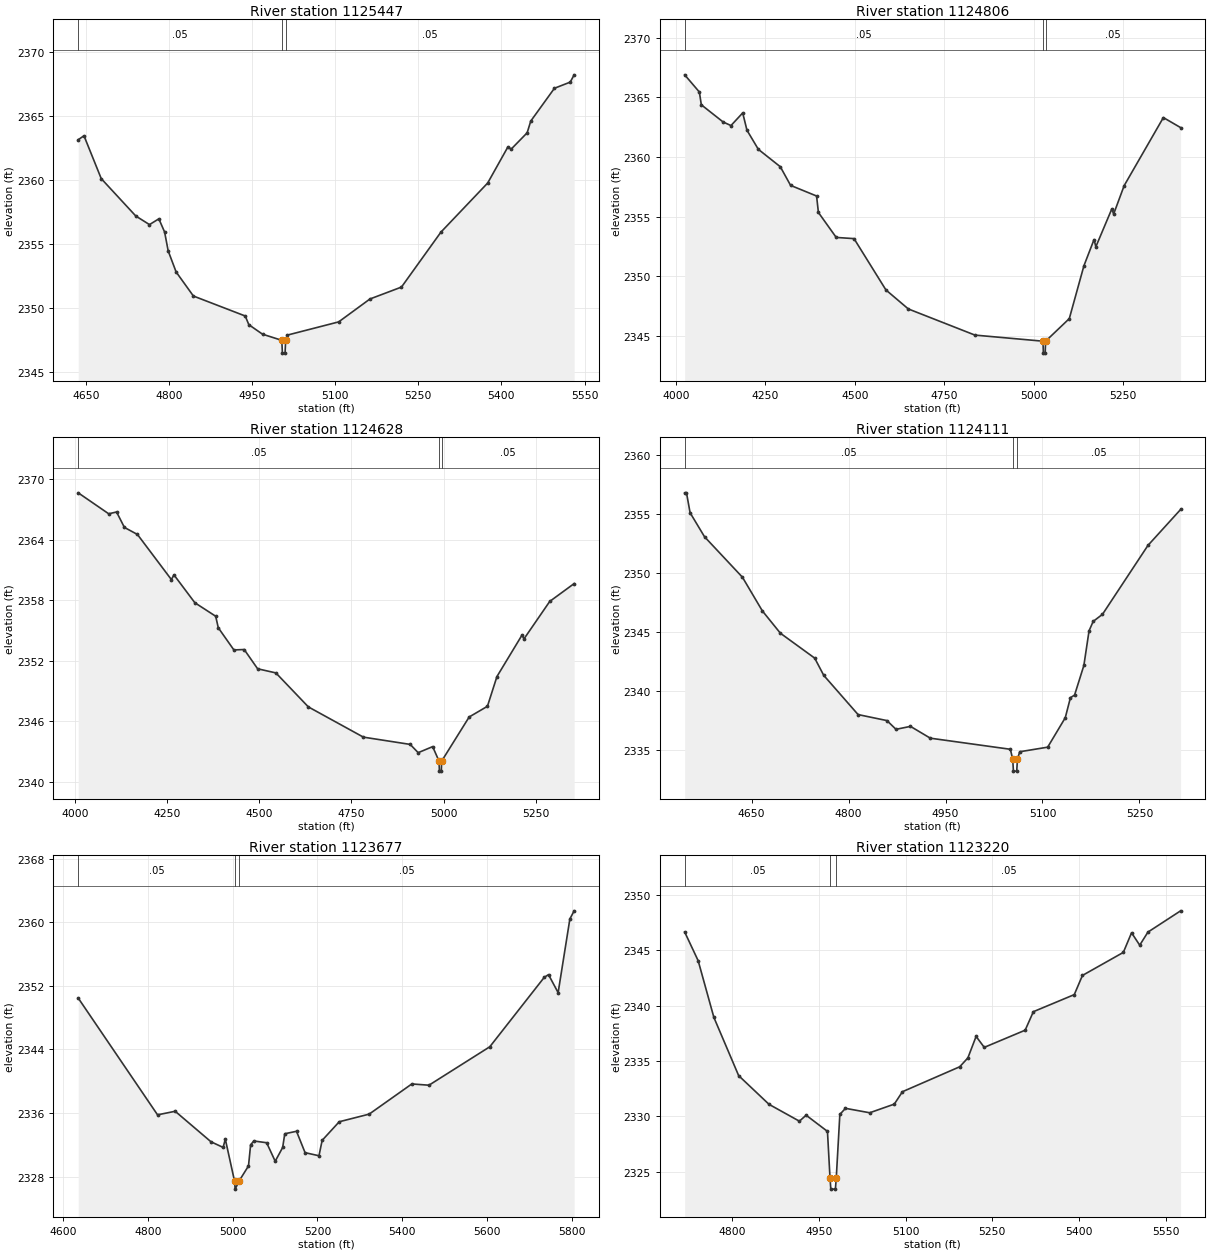
Type RM Length L Ch R = 1,1125447,641,641,641
BEGIN DESCRIPTION:
Clear Fork Brazos Rv 424.0
END DESCRIPTION:
XS GIS Cut Line= 3
      1276654.98      6935538.01      1277005.00      6935438.00
      1277404.98      6935088.02
#Sta/Elev= 30
  4635.8 2363.15  4646.2 2363.46  4677.4 2360.11  4739.8 2357.19  4764.5 2356.52
  4781.4 2356.97  4791.8 2355.94  4798.3 2354.46  4812.6 2352.82  4843.8 2350.94
  4937.4 2349.38  4943.9 2348.70  4968.6 2347.96  5003.4 2347.48  5004.5 2346.48
  5009.3 2346.48  5010.4 2347.48  5013.6 2347.89  5106.1 2348.92  5162.6 2350.71
  5219.5 2351.64  5290.7 2355.93  5375.2 2359.77  5411.3 2362.56  5417.9 2362.43
  5446.4 2363.69  5453.0 2364.61  5495.7 2367.17  5524.2 2367.65  5531.3 2368.22
#Mann=3,-1,0
  4635.8    0.05       0  5003.4   0.035       0  5010.4    0.05       0
Bank Sta=5003.4,5010.4
Exp/Cntr=0.3,0.1

Type RM Length L Ch R = 1,1124806,178,178,178
BEGIN DESCRIPTION:
Mapping XS 88d91db5
END DESCRIPTION:
XS GIS Cut Line= 4
      1276476.76      6935624.51      1276807.51      6935770.66
      1277789.47      6935978.33      1277809.08      6935983.24
#Sta/Elev= 30
  4024.8 2366.89  4065.8 2365.45  4071.3 2364.38  4132.2 2362.94  4154.1 2362.64
  4186.9 2363.70  4198.8 2362.25  4230.6 2360.65  4292.0 2359.19  4320.7 2357.63
  4393.3 2356.74  4398.4 2355.36  4448.2 2353.27  4497.9 2353.17  4587.1 2348.87
  4649.6 2347.28  4835.7 2345.09  5025.8 2344.58  5026.9 2343.58  5031.9 2343.58
  5033.1 2344.58  5099.3 2346.47  5140.2 2350.90  5168.4 2353.09  5173.5 2352.49
  5218.1 2355.66  5223.2 2355.23  5252.6 2357.61  5362.1 2363.31  5410.3 2362.47
#Mann=3,-1,0
  4024.8    0.05       0  5025.8    0.03       0  5033.1    0.05       0
Bank Sta=5025.8,5033.1
Exp/Cntr=0.3,0.1

Type RM Length L Ch R = 1,1124628,517,517,517
BEGIN DESCRIPTION:
Mapping XS 28d6877d
END DESCRIPTION:
XS GIS Cut Line= 3
      1276597.26      6936237.31      1276899.81      6935939.88
      1277799.73      6936132.17
#Sta/Elev= 30
  4009.2 2368.65  4091.9 2366.57  4113.2 2366.75  4134.4 2365.22  4169.8 2364.52
  4261.7 2360.05  4268.8 2360.51  4325.4 2357.75  4381.9 2356.41  4388.9 2355.27
  4431.2 2353.07  4459.2 2353.11  4495.6 2351.20  4545.1 2350.79  4633.1 2347.42
  4782.4 2344.42  4909.2 2343.70  4930.9 2342.88  4970.1 2343.48  4987.3 2342.05
  4988.5 2341.05  4993.5 2341.05  4994.6 2342.05  5069.1 2346.42  5118.6 2347.48
  5144.4 2350.43  5212.5 2354.55  5217.6 2354.16  5287.5 2357.88  5353.7 2359.65
#Mann=3,-1,0
  4009.2    0.05       0  4987.3    0.03       0  4994.6    0.05       0
Bank Sta=4987.3,4994.6
Exp/Cntr=0.3,0.1

Type RM Length L Ch R = 1,1124111,434,434,434
BEGIN DESCRIPTION:
Clear Fork Brazos Rv 421.0
END DESCRIPTION:
XS GIS Cut Line= 3
      1277205.00      6936688.00      1277605.00      6936488.00
      1277805.02      6936237.97
#Sta/Elev= 30
  4546.4 2356.81  4549.2 2356.81  4554.8 2355.12  4577.1 2353.09  4635.8 2349.66
  4666.6 2346.81  4694.5 2344.92  4747.6 2342.81  4761.6 2341.35  4814.7 2338.03
  4859.4 2337.52  4873.4 2336.78  4895.8 2337.03  4926.5 2336.03  5050.4 2335.09
  5054.0 2334.24  5055.1 2333.24  5060.2 2333.24  5061.3 2334.24  5064.8 2334.88
  5108.1 2335.27  5135.3 2337.76  5143.3 2339.46  5149.7 2339.68  5164.1 2342.19
  5172.1 2345.12  5178.5 2345.92  5192.9 2346.52  5263.3 2352.36  5313.8 2355.40
#Mann=3,-1,0
  4546.4    0.05       0  5054.0    0.05       0  5061.3    0.05       0
Bank Sta=5054,5061.3
Exp/Cntr=0.3,0.1

Type RM Length L Ch R = 1,1123677,457,457,457
BEGIN DESCRIPTION:
Clear Fork Brazos Rv 420.0
END DESCRIPTION:
XS GIS Cut Line= 3
      1277355.03      6936887.99      1277705.00      6936788.00
      1278505.00      6936688.00
#Sta/Elev= 30
  4635.5 2350.47  4822.7 2335.77  4864.3 2336.22  4948.8 2332.38  4977.4 2331.67
  4982.6 2332.71  5004.4 2327.42  5005.8 2326.42  5014.8 2327.42  5037.3 2329.34
  5042.3 2332.00  5049.9 2332.48  5080.1 2332.26  5100.3 2329.93  5117.9 2331.66
  5122.9 2333.39  5150.6 2333.70  5170.8 2331.01  5203.6 2330.62  5211.1 2332.56
  5251.4 2334.90  5322.0 2335.86  5422.7 2339.66  5463.1 2339.50  5606.7 2344.34
  5735.2 2353.08  5745.2 2353.42  5767.9 2351.15  5795.6 2360.43  5805.7 2361.45
#Mann=3,-1,0
  4635.5    0.05       0  5004.4    0.05       0  5014.8    0.05       0
Bank Sta=5004.4,5014.8
Exp/Cntr=0.3,0.1

Type RM Length L Ch R = 1,1123220,456,456,456
BEGIN DESCRIPTION:
Clear Fork Brazos Rv 419.0
END DESCRIPTION:
XS GIS Cut Line= 3
      1277405.00      6936938.00      1277555.00      6937188.00
      1277954.98      6937587.98
#Sta/Elev= 30
  4718.2 2346.64  4741.5 2344.05  4768.7 2338.93  4811.5 2333.68  4864.0 2331.09
  4916.5 2329.57  4928.1 2330.11  4965.0 2328.65  4969.4 2324.44  4970.8 2323.44
  4978.7 2323.44  4980.2 2324.44  4986.4 2330.18  4996.1 2330.73  5038.0 2330.33
  5080.5 2331.11  5094.6 2332.23  5193.6 2334.48  5207.7 2335.28  5221.9 2337.22
  5236.0 2336.23  5306.7 2337.78  5320.9 2339.45  5391.6 2340.99  5405.7 2342.72
  5476.4 2344.80  5490.6 2346.57  5504.7 2345.45  5518.9 2346.63  5575.4 2348.55
#Mann=3,-1,0
  4718.2    0.05       0  4969.4    0.03       0  4980.2    0.05       0
Bank Sta=4969.4,4980.2
Exp/Cntr=0.3,0.1

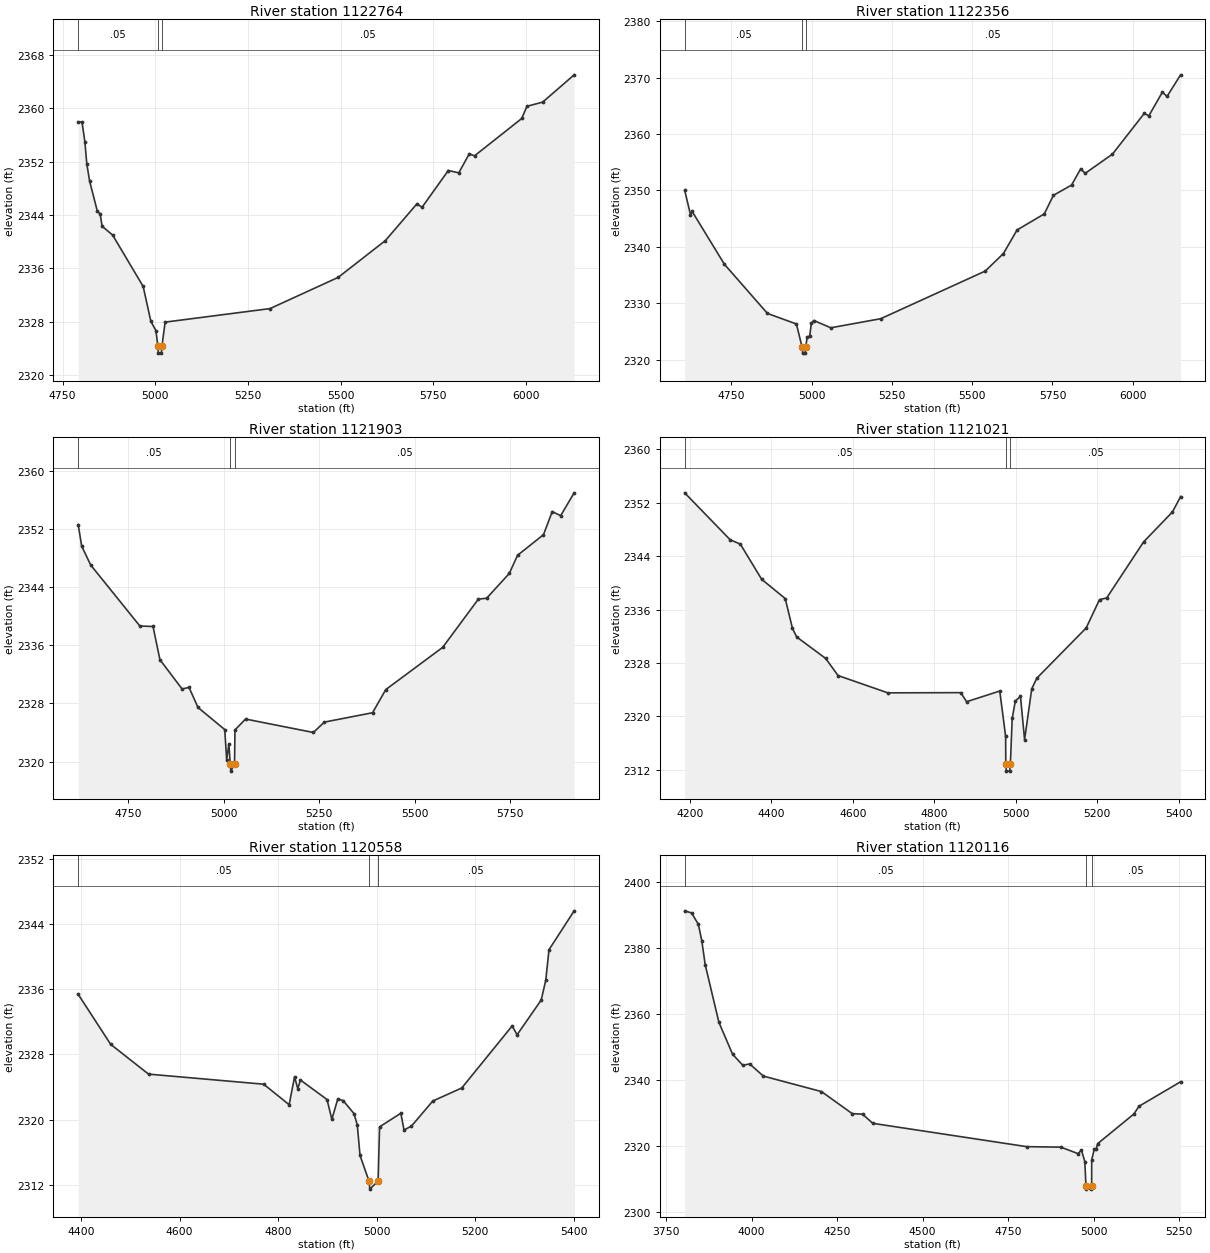
Type RM Length L Ch R = 1,1122764,408,408,408
BEGIN DESCRIPTION:
Clear Fork Brazos Rv 418.0
END DESCRIPTION:
XS GIS Cut Line= 3
      1276955.01      6937138.00      1277155.00      6937188.00
      1277954.99      6937987.99
#Sta/Elev= 30
  4792.0 2357.98  4802.3 2357.93  4810.0 2354.97  4815.2 2351.64  4822.9 2349.04
  4843.5 2344.59  4851.3 2344.15  4856.4 2342.31  4884.8 2340.99  4967.2 2333.28
  4987.8 2328.07  5001.7 2326.64  5006.8 2324.28  5008.3 2323.28  5016.2 2323.28
  5017.7 2324.28  5026.4 2327.93  5309.3 2329.96  5493.1 2334.64  5620.4 2340.16
  5705.3 2345.66  5719.4 2345.16  5790.1 2350.67  5818.4 2350.32  5846.7 2353.18
  5860.8 2352.87  5988.1 2358.47  6002.2 2360.30  6044.7 2360.93  6129.5 2365.02
#Mann=3,-1,0
  4792.0    0.05       0  5006.8    0.03       0  5017.7    0.05       0
Bank Sta=5006.8,5017.7
Exp/Cntr=0.3,0.1

Type RM Length L Ch R = 1,1122356,453,453,453
BEGIN DESCRIPTION:
Clear Fork Brazos Rv 417.0
END DESCRIPTION:
XS GIS Cut Line= 3
      1276855.00      6937137.98      1276955.00      6937538.00
      1277755.00      6938338.00
#Sta/Elev= 30
  4605.2 2350.03  4623.3 2345.72  4628.4 2346.29  4728.9 2336.92  4862.9 2328.21
  4953.1 2326.34  4970.8 2322.18  4972.3 2321.18  4980.2 2321.18  4981.7 2322.18
  4986.6 2324.04  4994.3 2324.20  4999.5 2326.46  5007.2 2326.96  5060.0 2325.67
  5215.5 2327.28  5540.8 2335.72  5597.4 2338.83  5639.8 2343.00  5724.6 2345.85
  5752.9 2349.14  5809.5 2350.96  5837.8 2353.84  5851.9 2353.04  5936.8 2356.44
  6035.8 2363.66  6049.9 2363.22  6092.3 2367.44  6106.5 2366.65  6148.9 2370.49
#Mann=3,-1,0
  4605.2    0.05       0  4970.8    0.03       0  4981.7    0.05       0
Bank Sta=4970.8,4981.7
Exp/Cntr=0.3,0.1

Type RM Length L Ch R = 1,1121903,882,882,882
BEGIN DESCRIPTION:
Clear Fork Brazos Rv 416.0
END DESCRIPTION:
XS GIS Cut Line= 3
      1276354.97      6937687.99      1276705.00      6937838.00
      1277505.00      6938288.00
#Sta/Elev= 30
  4618.9 2352.61  4628.0 2349.65  4651.6 2347.05  4780.3 2338.66  4814.8 2338.59
  4832.9 2334.02  4890.9 2329.99  4909.1 2330.20  4932.6 2327.44  5002.6 2324.40
  5007.7 2320.21  5013.4 2322.42  5017.1 2319.68  5018.6 2318.68  5028.2 2319.68
  5029.4 2324.35  5057.1 2325.85  5234.6 2324.00  5263.6 2325.43  5389.8 2326.72
  5424.2 2329.90  5573.4 2335.72  5666.8 2342.36  5688.4 2342.48  5747.7 2345.89
  5769.4 2348.39  5837.3 2351.23  5860.2 2354.41  5882.2 2353.84  5917.6 2356.99
#Mann=3,-1,0
  4618.9    0.05       0  5017.1    0.05       0  5028.2    0.05       0
Bank Sta=5017.1,5028.2
Exp/Cntr=0.3,0.1

Type RM Length L Ch R = 1,1121021,463,463,463
BEGIN DESCRIPTION:
Clear Fork Brazos Rv 414.0
END DESCRIPTION:
XS GIS Cut Line= 3
      1276155.02      6938338.00      1276955.00      6938488.00
      1277354.97      6938538.00
#Sta/Elev= 30
  4187.7 2353.50  4299.6 2346.45  4324.2 2345.82  4376.7 2340.54  4434.4 2337.66
  4452.2 2333.19  4462.4 2331.91  4533.6 2328.69  4564.1 2326.12  4686.2 2323.53
  4865.1 2323.56  4879.5 2322.20  4960.9 2323.80  4975.3 2317.01  4975.7 2312.80
  4977.2 2311.80  4985.4 2311.80  4986.9 2312.80  4991.4 2319.69  4999.1 2322.31
  5011.7 2322.99  5021.8 2316.51  5039.4 2324.14  5052.0 2325.74  5172.9 2333.25
  5205.7 2337.50  5223.3 2337.75  5314.0 2346.16  5384.6 2350.63  5404.7 2352.94
#Mann=3,-1,0
  4187.7    0.05       0  4975.7    0.03       0  4986.9    0.05       0
Bank Sta=4975.7,4986.9
Exp/Cntr=0.3,0.1

Type RM Length L Ch R = 1,1120558,442,442,442
BEGIN DESCRIPTION:
Clear Fork Brazos Rv 413.0
END DESCRIPTION:
XS GIS Cut Line= 3
      1276355.04      6939187.98      1276905.00      6938938.00
      1277254.98      6938738.01
#Sta/Elev= 30
  4394.1 2335.38  4460.0 2329.24  4536.9 2325.58  4770.8 2324.34  4822.5 2321.82
  4833.4 2325.24  4840.0 2323.80  4845.5 2324.85  4899.4 2322.46  4909.2 2320.03
  4921.3 2322.53  4932.3 2322.32  4954.3 2320.72  4960.9 2319.33  4966.4 2315.59
  4984.6 2312.45  4986.4 2311.45  5003.2 2312.45  5006.1 2319.10  5049.3 2320.77
  5055.8 2318.72  5070.9 2319.19  5114.1 2322.27  5173.1 2323.88  5275.4 2331.50
  5285.4 2330.41  5334.4 2334.68  5343.7 2337.13  5350.2 2340.86  5401.3 2345.64
#Mann=3,-1,0
  4394.1    0.05       0  4984.6    0.05       0  5003.2    0.05       0
Bank Sta=4984.6,5003.2
Exp/Cntr=0.3,0.1

Type RM Length L Ch R = 1,1120116,442,442,442
BEGIN DESCRIPTION:
Clear Fork Brazos Rv 412.0
END DESCRIPTION:
XS GIS Cut Line= 3
      1275955.05      6939238.00      1277155.00      6939238.00
      1277355.04      6939087.97
#Sta/Elev= 30
  3804.6 2391.41  3824.6 2390.78  3844.6 2387.33  3854.6 2382.36  3864.6 2375.10
  3904.6 2357.64  3944.6 2347.96  3974.6 2344.59  3994.6 2345.02  4034.6 2341.33
  4204.6 2336.63  4294.6 2329.94  4324.6 2329.79  4354.6 2327.01  4804.6 2319.94
  4904.6 2319.79  4954.6 2317.83  4964.6 2318.89  4974.6 2315.41  4977.8 2308.07
  4979.4 2307.07  4992.9 2307.07  4994.5 2308.07  4994.6 2315.99  5002.1 2319.09
  5007.7 2319.09  5011.8 2320.83  5118.1 2329.85  5132.7 2332.17  5254.6 2339.61
#Mann=3,-1,0
  3804.6    0.05       0  4977.8    0.05       0  4994.5    0.05       0
Bank Sta=4977.8,4994.5
Exp/Cntr=0.3,0.1