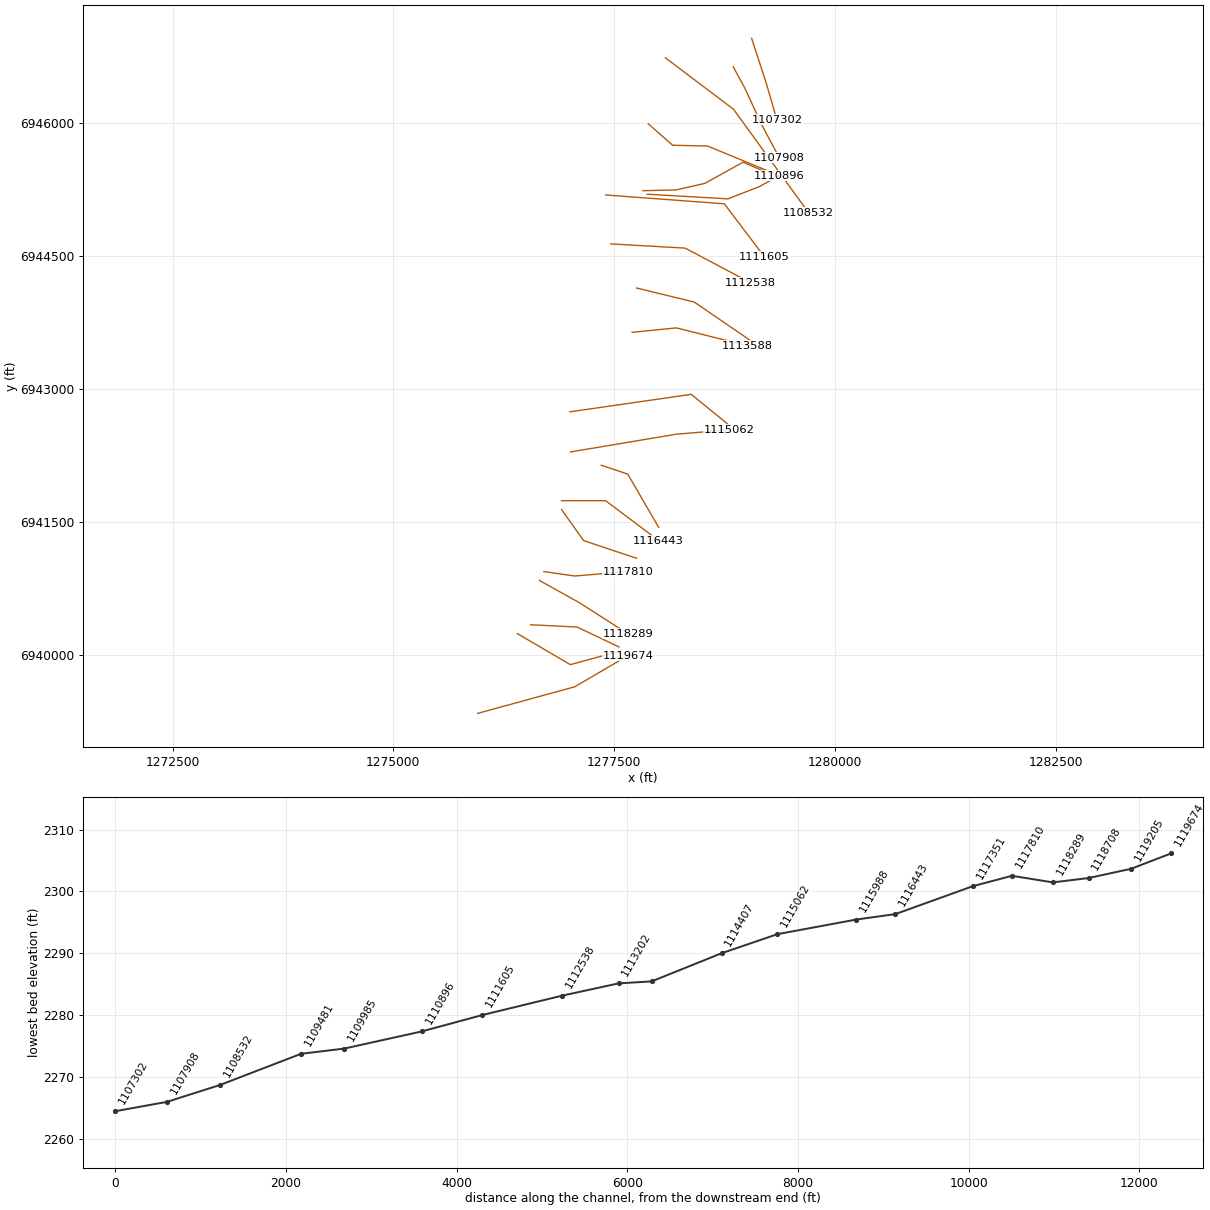
HEC-RAS study Clear Fork Brazos Rv.prj: Clear Fork Brazos Rv Base Level Engineering

--- Clear Fork Brazos Rv.g01 (geometry) --- (continued)

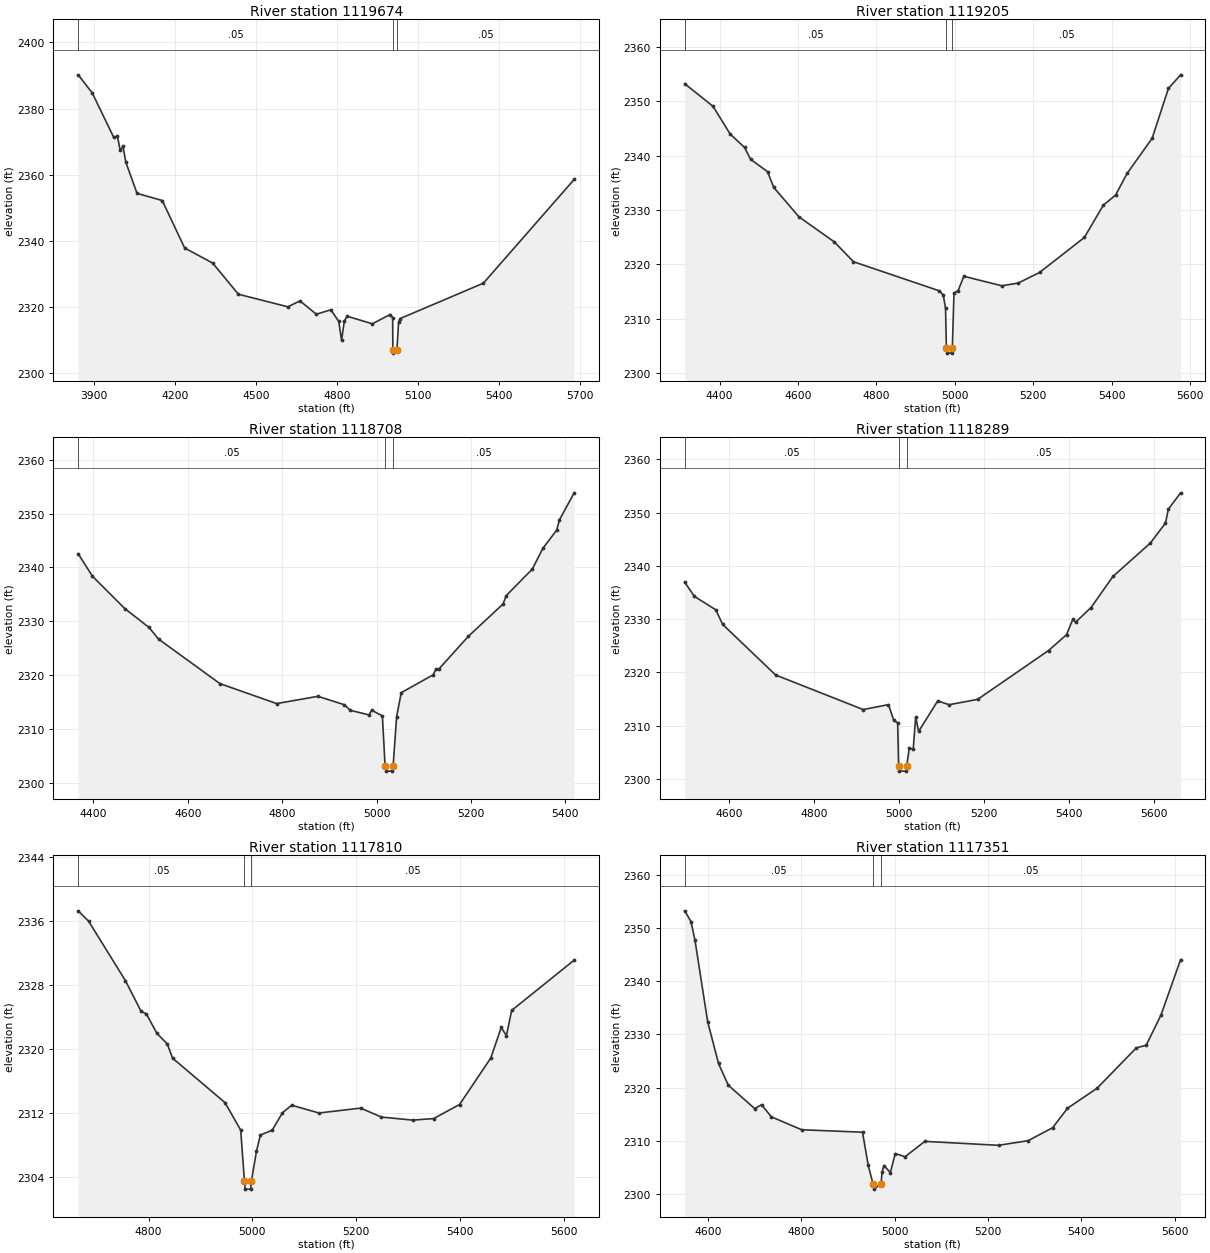
Type RM Length L Ch R = 1,1119674,469,469,469
BEGIN DESCRIPTION:
Clear Fork Brazos Rv 411.0
END DESCRIPTION:
XS GIS Cut Line= 3
      1275955.04      6939338.01      1277055.00      6939638.00
      1277655.04      6939988.02
#Sta/Elev= 30
  3842.9 2390.23  3894.7 2384.78  3974.2 2371.35  3988.0 2371.66  3998.3 2367.40
  4008.7 2368.59  4019.1 2363.84  4060.5 2354.41  4153.8 2352.26  4236.7 2337.91
  4340.4 2333.36  4435.4 2323.95  4618.5 2320.14  4663.4 2321.94  4723.9 2317.90
  4777.5 2319.24  4806.8 2315.73  4817.2 2310.05  4827.6 2315.93  4837.9 2317.29
  4931.2 2315.01  4996.7 2317.82  5006.2 2316.90  5007.0 2307.15  5008.6 2306.15
  5022.1 2307.15  5028.1 2315.47  5033.9 2316.59  5341.9 2327.28  5677.7 2358.62
#Mann=3,-1,0
  3842.9    0.05       0  5007.0    0.05       0  5022.1    0.05       0
Bank Sta=5007,5022.1
Exp/Cntr=0.3,0.1

Type RM Length L Ch R = 1,1119205,497,497,497
BEGIN DESCRIPTION:
Clear Fork Brazos Rv 410.0
END DESCRIPTION:
XS GIS Cut Line= 3
      1276404.96      6940238.02      1277005.00      6939888.00
      1277555.04      6940038.01
#Sta/Elev= 30
  4310.9 2353.24  4383.3 2349.08  4426.7 2344.00  4463.5 2341.52  4479.2 2339.32
  4522.2 2337.06  4537.9 2334.17  4602.4 2328.74  4692.6 2324.13  4741.4 2320.48
  4960.5 2315.12  4970.4 2314.34  4976.2 2311.91  4978.3 2304.66  4979.9 2303.66
  4991.9 2303.66  4993.5 2304.66  4997.7 2314.72  5008.2 2315.15  5022.8 2317.80
  5119.6 2316.06  5161.0 2316.54  5216.3 2318.52  5330.3 2324.95  5378.7 2330.91
  5409.8 2332.74  5439.2 2336.73  5503.1 2343.20  5544.6 2352.37  5575.7 2354.88
#Mann=3,-1,0
  4310.9    0.05       0  4978.3    0.05       0  4993.5    0.05       0
Bank Sta=4978.3,4993.5
Exp/Cntr=0.3,0.1

Type RM Length L Ch R = 1,1118708,419,419,419
BEGIN DESCRIPTION:
Clear Fork Brazos Rv 409.0
END DESCRIPTION:
XS GIS Cut Line= 3
      1276555.05      6940338.00      1277081.58      6940312.19
      1277555.01      6940087.99
#Sta/Elev= 30
  4367.7 2342.52  4397.7 2338.37  4466.3 2332.36  4517.8 2328.84  4537.9 2326.69
  4668.0 2318.42  4788.2 2314.71  4875.8 2316.06  4931.8 2314.49  4944.1 2313.47
  4984.0 2312.61  4989.6 2313.48  5012.3 2312.42  5018.0 2303.17  5019.8 2302.17
  5033.3 2302.17  5035.1 2303.17  5042.5 2312.30  5052.3 2316.74  5119.9 2320.05
  5126.0 2321.13  5131.6 2321.09  5194.3 2327.18  5268.1 2333.21  5274.8 2334.76
  5330.2 2339.70  5352.3 2343.52  5381.8 2346.92  5387.3 2348.78  5418.7 2353.84
#Mann=3,-1,0
  4367.7    0.05       0  5018.0    0.05       0  5035.1    0.05       0
Bank Sta=5018,5035.1
Exp/Cntr=0.3,0.1

Type RM Length L Ch R = 1,1118289,479,479,479
BEGIN DESCRIPTION:
Clear Fork Brazos Rv 408.0
END DESCRIPTION:
XS GIS Cut Line= 3
      1276655.02      6940837.99      1277105.00      6940588.00
      1277655.02      6940237.99
#Sta/Elev= 30
  4496.0 2336.94  4518.9 2334.26  4569.2 2331.74  4585.2 2329.01  4709.9 2319.51
  4915.8 2313.02  4975.3 2313.94  4987.9 2310.99  4997.0 2310.53  4999.3 2302.46
  5001.3 2301.46  5016.3 2301.46  5018.3 2302.46  5024.3 2305.72  5033.6 2305.60
  5039.5 2311.65  5046.3 2308.91  5091.2 2314.63  5118.3 2313.93  5185.2 2314.93
  5352.0 2324.10  5394.3 2327.07  5409.5 2330.03  5415.5 2329.41  5451.9 2332.16
  5503.5 2338.00  5591.6 2344.28  5627.1 2348.02  5633.9 2350.64  5662.7 2353.70
#Mann=3,-1,0
  4496.0    0.05       0  4999.3    0.03       0  5018.3    0.05       0
Bank Sta=4999.3,5018.3
Exp/Cntr=0.3,0.1

Type RM Length L Ch R = 1,1117810,459,459,459
BEGIN DESCRIPTION:
Clear Fork Brazos Rv 407.0
END DESCRIPTION:
XS GIS Cut Line= 3
      1276705.04      6940937.99      1277055.00      6940888.00
      1277655.01      6940938.00
#Sta/Elev= 30
  4664.3 2337.29  4684.5 2335.98  4755.2 2328.58  4785.5 2324.73  4795.6 2324.42
  4815.8 2322.00  4836.0 2320.66  4846.1 2318.89  4947.1 2313.34  4977.4 2309.90
  4984.6 2303.53  4986.0 2302.53  4996.5 2302.53  4998.0 2303.53  5007.7 2307.24
  5015.3 2309.29  5037.9 2309.88  5057.9 2312.07  5075.5 2313.01  5128.2 2312.04
  5208.5 2312.65  5248.6 2311.53  5308.8 2311.15  5349.0 2311.34  5399.1 2313.10
  5459.3 2318.91  5479.4 2322.73  5489.4 2321.70  5499.5 2324.85  5619.9 2331.13
#Mann=3,-1,0
  4664.3    0.05       0  4984.6    0.05       0  4998.0    0.05       0
Bank Sta=4984.6,4998
Exp/Cntr=0.3,0.1

Type RM Length L Ch R = 1,1117351,908,908,908
BEGIN DESCRIPTION:
Clear Fork Brazos Rv 406.0
END DESCRIPTION:
XS GIS Cut Line= 3
      1276904.98      6941638.02      1277155.00      6941288.00
      1277755.00      6941088.00
#Sta/Elev= 30
  4550.3 2353.30  4563.8 2351.28  4572.4 2347.74  4599.5 2332.42  4622.8 2324.53
  4643.7 2320.44  4700.3 2316.03  4715.0 2316.76  4735.9 2314.48  4801.0 2312.04
  4931.3 2311.58  4943.6 2305.33  4953.8 2301.85  4955.7 2300.85  4971.2 2301.85
  4973.1 2304.08  4977.4 2305.30  4991.0 2303.97  5001.5 2307.55  5022.6 2306.96
  5064.8 2309.85  5222.9 2309.11  5286.1 2309.98  5338.8 2312.43  5370.5 2316.09
  5433.7 2319.85  5518.0 2327.47  5539.1 2327.97  5570.7 2333.63  5612.9 2344.12
#Mann=3,-1,0
  4550.3    0.05       0  4953.8    0.05       0  4971.2    0.05       0
Bank Sta=4953.8,4971.2
Exp/Cntr=0.3,0.1

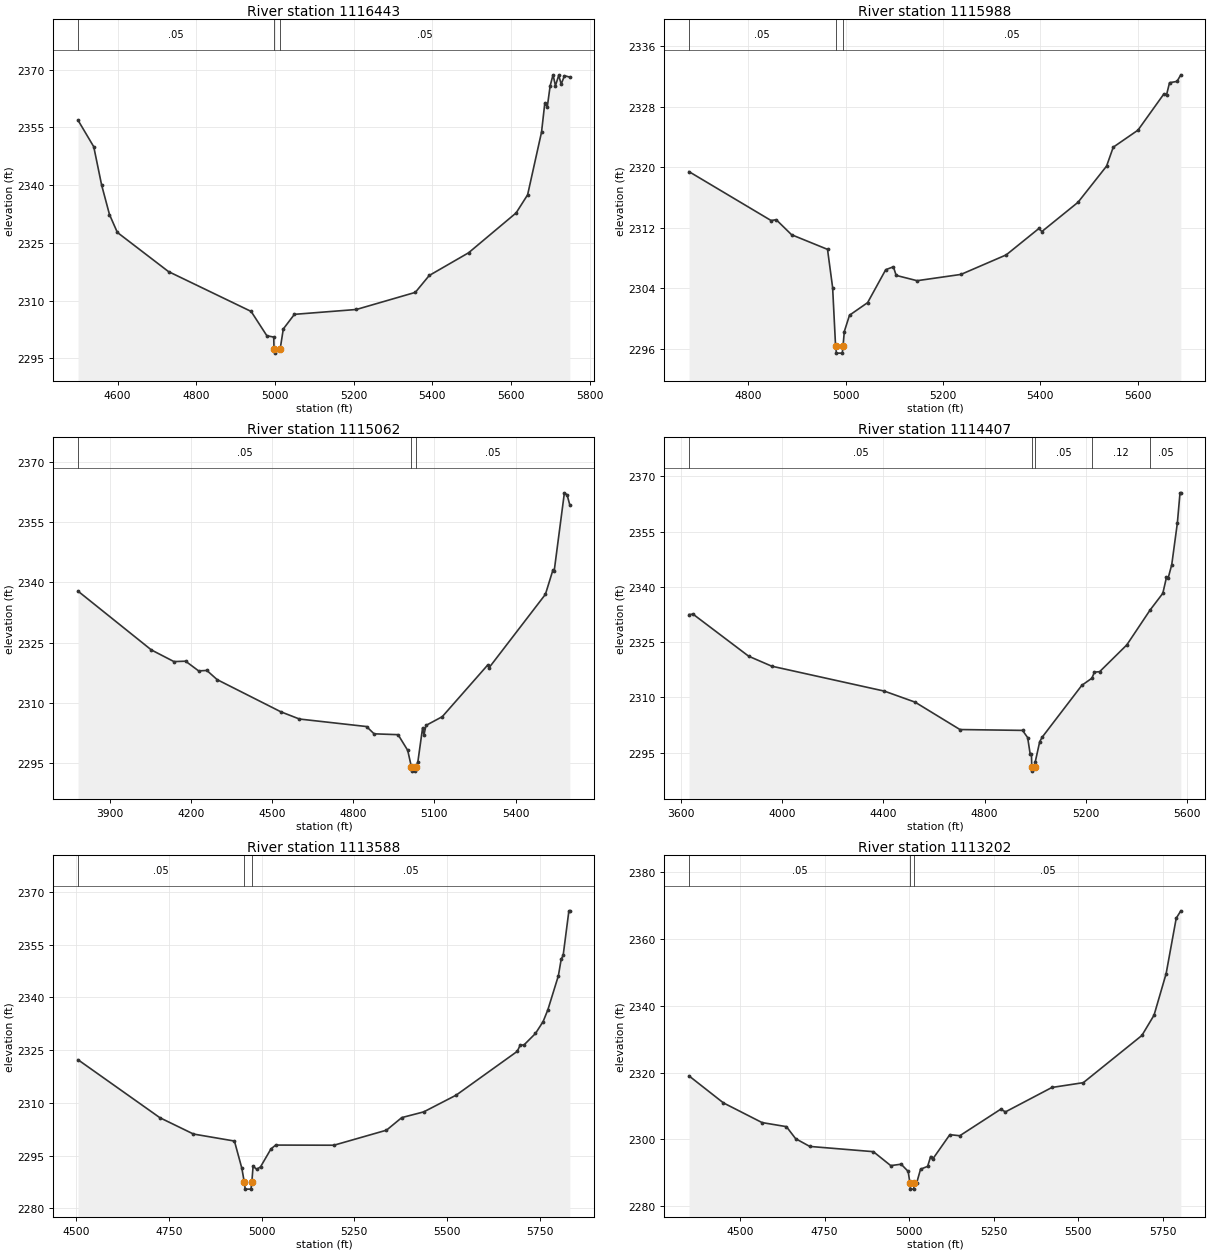
Type RM Length L Ch R = 1,1116443,455,455,455
BEGIN DESCRIPTION:
Clear Fork Brazos Rv 405.0
END DESCRIPTION:
XS GIS Cut Line= 3
      1276905.03      6941738.00      1277405.00      6941738.00
      1278005.02      6941287.98
#Sta/Elev= 30
  4499.4 2356.87  4539.4 2349.97  4559.4 2340.03  4579.4 2332.35  4599.4 2327.70
  4729.4 2317.52  4939.4 2307.17  4979.4 2300.85  4996.9 2300.50  4997.6 2297.33
  4999.4 2296.33  5013.1 2297.33  5021.2 2302.62  5049.4 2306.41  5206.7 2307.67
  5356.7 2312.12  5392.1 2316.51  5492.1 2322.41  5612.9 2332.77  5642.1 2337.47
  5677.5 2353.77  5685.8 2361.28  5692.1 2360.30  5699.4 2365.79  5706.7 2368.66
  5712.9 2365.83  5721.2 2368.54  5727.5 2366.24  5735.8 2368.43  5749.4 2368.06
#Mann=3,-1,0
  4499.4    0.05       0  4997.6    0.05       0  5013.1    0.05       0
Bank Sta=4997.6,5013.1
Exp/Cntr=0.3,0.1

Type RM Length L Ch R = 1,1115988,926,926,926
BEGIN DESCRIPTION:
Clear Fork Brazos Rv 404.0
END DESCRIPTION:
XS GIS Cut Line= 3
      1277354.95      6942138.02      1277655.00      6942038.00
      1278005.00      6941438.00
#Sta/Elev= 30
  4678.0 2319.44  4846.7 2312.98  4857.2 2313.09  4888.9 2311.10  4962.7 2309.17
  4973.2 2304.12  4979.2 2296.46  4981.0 2295.46  4993.0 2295.46  4994.7 2296.46
  4997.2 2298.31  5007.9 2300.47  5045.1 2302.13  5082.3 2306.48  5098.1 2306.87
  5103.8 2305.73  5146.8 2305.03  5237.0 2305.86  5330.0 2308.44  5397.4 2311.94
  5403.2 2311.52  5477.6 2315.39  5536.3 2320.17  5550.0 2322.67  5600.8 2324.92
  5653.8 2329.68  5659.5 2329.57  5665.7 2331.19  5681.0 2331.36  5688.9 2332.23
#Mann=3,-1,0
  4678.0    0.05       0  4979.2    0.05       0  4994.7    0.05       0
Bank Sta=4979.2,4994.7
Exp/Cntr=0.3,0.1

Type RM Length L Ch R = 1,1115062,655,655,655
BEGIN DESCRIPTION:
Clear Fork Brazos Rv 403.0
END DESCRIPTION:
XS GIS Cut Line= 3
      1277004.97      6942287.99      1278205.00      6942488.00
      1278805.04      6942538.00
#Sta/Elev= 30
  3782.1 2337.82  4053.3 2323.21  4137.0 2320.31  4180.0 2320.41  4228.2 2318.00
  4258.6 2318.11  4296.6 2315.83  4532.3 2307.83  4600.8 2306.04  4849.1 2304.17
  4877.0 2302.36  4965.7 2302.15  5001.2 2298.27  5015.2 2294.09  5017.0 2293.09
  5029.0 2293.09  5030.9 2294.09  5038.8 2295.35  5056.4 2303.88  5061.4 2302.07
  5068.9 2304.45  5129.1 2306.62  5297.2 2319.47  5302.2 2318.79  5510.5 2337.02
  5538.0 2343.00  5543.1 2342.88  5580.7 2362.25  5590.7 2361.74  5600.8 2359.23
#Mann=3,-1,0
  3782.1    0.05       0  5015.2    0.05       0  5030.9    0.05       0
Bank Sta=5015.2,5030.9
Exp/Cntr=0.3,0.1

Type RM Length L Ch R = 1,1114407,819,819,819
BEGIN DESCRIPTION:
Clear Fork Brazos Rv 402.0
END DESCRIPTION:
XS GIS Cut Line= 3
      1277001.66      6942741.08      1278374.23      6942937.96
      1278804.98      6942588.02
#Sta/Elev= 30
  3632.8 2332.51  3648.8 2332.61  3868.5 2321.19  3959.4 2318.49  4404.0 2311.72
  4525.2 2308.73  4702.4 2301.29  4949.5 2301.06  4969.7 2299.10  4979.6 2294.67
  4984.7 2294.61  4986.0 2291.00  4987.7 2290.00  4999.8 2291.00  5000.0 2292.61
  5017.3 2297.99  5027.1 2299.22  5183.7 2313.30  5223.4 2315.23  5233.2 2316.87
  5254.0 2317.00  5361.1 2324.26  5452.9 2333.72  5503.3 2338.27  5517.7 2342.59
  5524.1 2342.34  5538.5 2346.02  5560.8 2357.40  5571.2 2365.55  5574.4 2365.55
#Mann=5,-1,0
  3632.8    0.05       0  4986.0    0.05       0  4999.8    0.05       0
  5223.4    0.12       0  5452.9    0.05       0
Bank Sta=4986,4999.8
Exp/Cntr=0.3,0.1

Type RM Length L Ch R = 1,1113588,386,386,386
BEGIN DESCRIPTION:
Clear Fork Brazos Rv 400.0
END DESCRIPTION:
XS GIS Cut Line= 3
      1277704.97      6943638.00      1278205.00      6943688.00
      1279004.96      6943488.01
#Sta/Elev= 30
  4504.7 2322.28  4725.8 2305.77  4816.3 2301.13  4926.8 2299.14  4946.9 2291.34
  4953.5 2287.35  4955.8 2285.45  4971.4 2285.45  4973.7 2287.35  4977.1 2291.96
  4987.1 2291.10  4997.2 2291.79  5025.3 2296.89  5038.1 2297.99  5195.3 2297.95
  5337.1 2302.23  5378.3 2305.81  5437.6 2307.44  5525.2 2312.21  5690.1 2324.68
  5697.8 2326.45  5708.1 2326.49  5739.1 2329.76  5759.7 2333.14  5772.6 2336.52
  5800.9 2346.18  5808.6 2350.93  5813.8 2351.97  5829.3 2364.67  5831.8 2364.67
#Mann=3,-1,0
  4504.7    0.05       0  4953.5    0.05       0  4973.7    0.05       0
Bank Sta=4953.5,4973.7
Exp/Cntr=0.3,0.1

Type RM Length L Ch R = 1,1113202,664,664,664
BEGIN DESCRIPTION:
Clear Fork Brazos Rv 399.0
END DESCRIPTION:
XS GIS Cut Line= 3
      1277754.98      6944138.00      1278409.72      6943978.72
      1279055.04      6943537.98
#Sta/Elev= 30
  4348.8 2319.02  4450.6 2310.94  4564.9 2305.05  4637.0 2303.83  4664.4 2300.22
  4706.1 2297.91  4894.3 2296.34  4945.7 2292.17  4976.6 2292.59  4997.2 2290.44
  5002.5 2287.03  5004.0 2285.13  5013.7 2285.13  5015.2 2287.03  5022.6 2287.03
  5033.9 2291.08  5054.9 2291.95  5063.8 2294.89  5069.8 2294.11  5120.6 2301.43
  5150.1 2301.11  5271.2 2309.05  5285.2 2308.25  5422.7 2315.56  5515.5 2316.99
  5688.9 2331.12  5724.8 2337.18  5760.7 2349.66  5790.5 2366.21  5804.1 2368.42
#Mann=3,-1,0
  4348.8    0.05       0  5002.5    0.05       0  5015.2    0.05       0
Bank Sta=5002.5,5015.2
Exp/Cntr=0.3,0.1

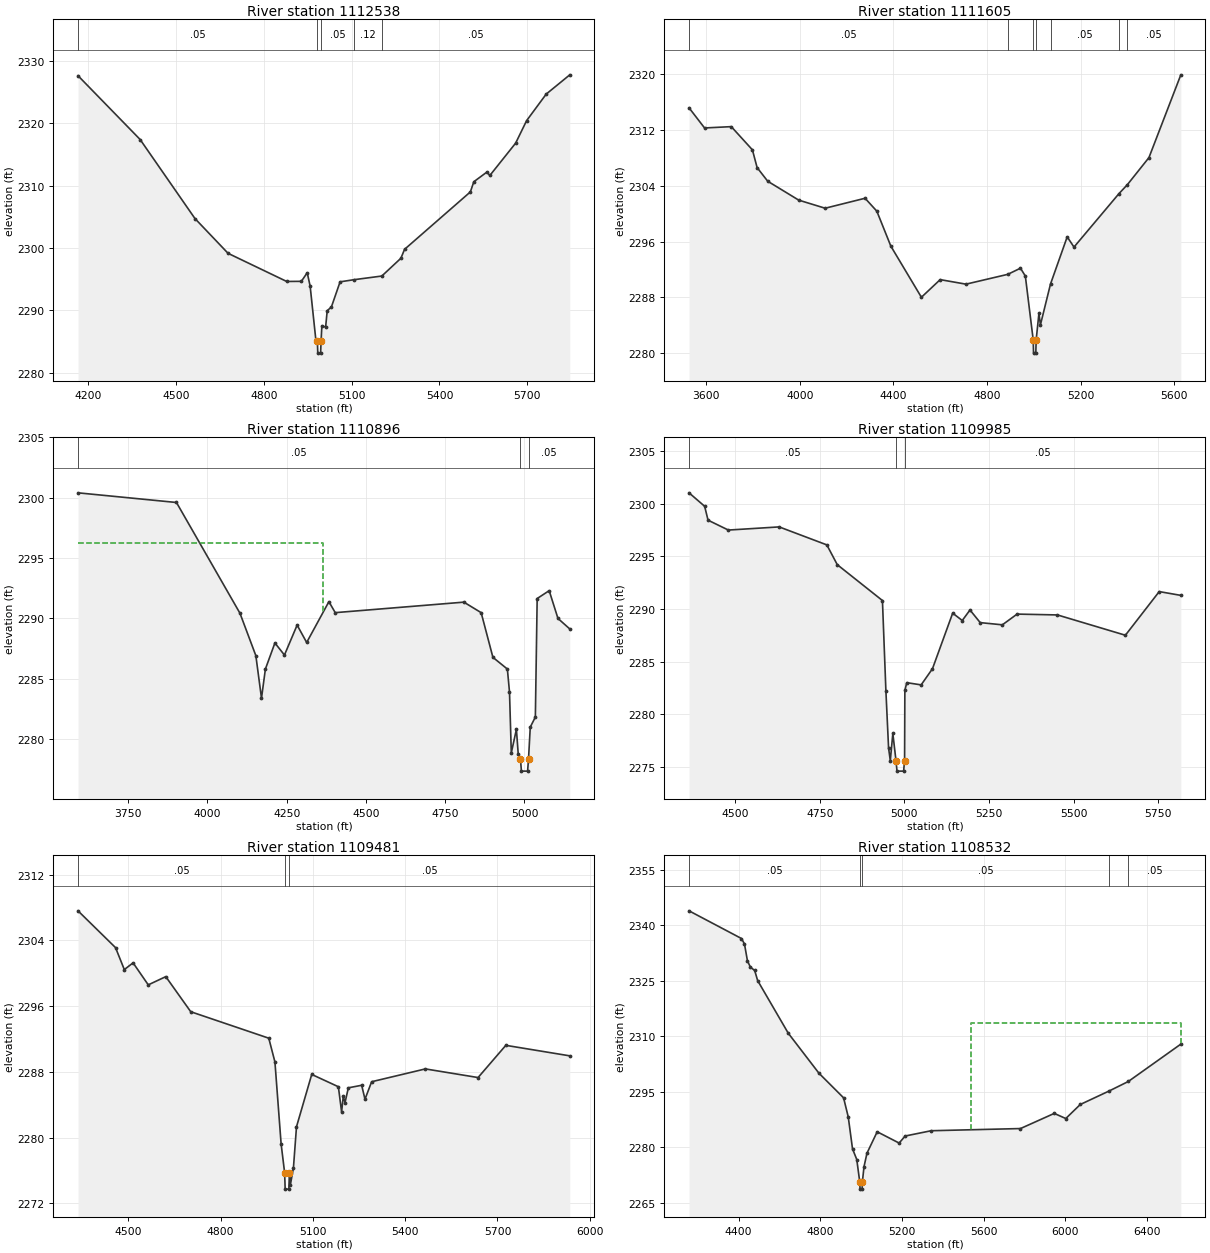
Type RM Length L Ch R = 1,1112538,933,933,933
BEGIN DESCRIPTION:
Clear Fork Brazos Rv 398.0
END DESCRIPTION:
XS GIS Cut Line= 3
      1277463.07      6944635.73      1278305.00      6944588.00
      1279045.56      6944197.71
#Sta/Elev= 30
  4164.9 2327.62  4377.2 2317.39  4564.5 2304.72  4677.7 2299.14  4878.0 2294.63
  4928.1 2294.65  4948.1 2296.03  4958.1 2293.89  4978.1 2285.04  4982.8 2285.04
  4984.2 2283.14  4993.9 2283.14  4995.4 2285.04  4998.2 2287.54  5011.0 2287.31
  5016.4 2289.94  5030.8 2290.55  5060.4 2294.57  5109.0 2294.92  5203.0 2295.50
  5268.2 2298.35  5280.7 2299.78  5505.6 2308.99  5517.4 2310.62  5562.1 2312.17
  5572.1 2311.62  5660.3 2316.81  5697.7 2320.41  5764.7 2324.67  5845.3 2327.76
#Mann=5,-1,0
  4164.9    0.05       0  4982.8    0.03       0  4995.4    0.05       0
  5109.0    0.12       0  5203.0    0.05       0
Bank Sta=4982.8,4995.4
Exp/Cntr=0.3,0.1

Type RM Length L Ch R = 1,1111605,709,709,709
BEGIN DESCRIPTION:
Clear Fork Brazos Rv 397.0
END DESCRIPTION:
XS GIS Cut Line= 3
      1277404.97      6945188.00      1278748.83      6945087.86
      1279205.00      6944487.99
#Sta/Elev= 30
  3527.0 2315.19  3593.3 2312.30  3707.5 2312.49  3797.8 2309.16  3817.8 2306.62
  3863.2 2304.66  3995.7 2301.95  4108.6 2300.79  4279.1 2302.22  4329.3 2300.37
  4389.4 2295.34  4519.8 2288.02  4600.0 2290.55  4710.3 2289.90  4889.0 2291.31
  4943.1 2292.19  4963.9 2291.06  4997.5 2281.91  4998.9 2280.01  5008.6 2280.01
  5010.1 2281.91  5022.0 2285.72  5028.3 2284.06  5071.4 2289.92  5142.7 2296.68
  5171.8 2295.22  5364.3 2302.90  5399.4 2304.15  5492.0 2308.05  5628.2 2319.92
#Mann=7,-1,0
  3527.0    0.05       0  4889.0    0.12       0  4997.5    0.07       0
  5010.1    0.12       0  5071.4    0.05       0  5364.3    0.12       0
  5399.4    0.05       0
Bank Sta=4997.5,5010.1
Exp/Cntr=0.3,0.1

Type RM Length L Ch R = 1,1110896,911,911,911
BEGIN DESCRIPTION:
Mapping XS 7b7e6cbb
END DESCRIPTION:
XS GIS Cut Line= 4
      1277874.90      6945196.12      1278789.36      6945143.95
      1279145.31      6945282.04      1279367.68      6945403.88
#Sta/Elev= 30
  3591.6 2300.40  3902.2 2299.60  4102.5 2290.43  4152.6 2286.92  4170.4 2283.40
  4182.7 2285.81  4212.7 2287.97  4242.8 2286.97  4282.8 2289.45  4312.9 2288.01
  4383.0 2291.39  4403.0 2290.48  4808.8 2291.35  4863.3 2290.48  4900.4 2286.78
  4946.0 2285.81  4952.7 2283.92  4958.4 2278.87  4974.5 2280.82  4980.2 2278.79
  4987.3 2278.36  4990.3 2277.36  5009.8 2277.36  5012.7 2278.36  5018.2 2281.00
  5034.3 2281.84  5040.0 2291.65  5077.9 2292.30  5105.6 2290.00  5142.9 2289.13
#Mann=3,-1,0
  3591.6    0.05       0  4987.3    0.05       0  5012.7    0.05       0
#XS Ineff=2,0
    0.00 4364.60 2296.28 5635.40    0.00 2296.28
Permanent Ineff=
       F       F
Bank Sta=4987.3,5012.7
Exp/Cntr=0.3,0.1

Type RM Length L Ch R = 1,1109985,504,504,504
BEGIN DESCRIPTION:
Mapping XS d10d7a7d
END DESCRIPTION:
XS GIS Cut Line= 5
      1277828.92      6945236.01      1278206.33      6945245.22
      1278528.53      6945318.86      1278960.80      6945557.36
      1279191.15      6945458.98
#Sta/Elev= 30
  4364.2 2301.04  4410.3 2299.76  4420.3 2298.44  4480.3 2297.50  4630.4 2297.80
  4771.1 2296.09  4801.9 2294.21  4935.3 2290.80  4945.5 2282.22  4953.4 2276.78
  4958.5 2275.58  4966.0 2278.16  4975.3 2275.58  4978.3 2274.58  4997.8 2274.58
  5000.7 2275.58  5001.5 2282.25  5007.1 2282.99  5049.6 2282.78  5083.1 2284.32
  5142.7 2289.60  5171.0 2288.90  5193.8 2289.90  5224.0 2288.70  5289.4 2288.49
  5332.9 2289.51  5452.1 2289.43  5652.7 2287.50  5752.6 2291.65  5816.4 2291.29
#Mann=3,-1,0
  4364.2    0.05       0  4975.3    0.05       0  5000.7    0.05       0
Bank Sta=4975.3,5000.7
Exp/Cntr=0.3,0.1

Type RM Length L Ch R = 1,1109481,949,949,949
BEGIN DESCRIPTION:
Mapping XS bec8f91c
END DESCRIPTION:
XS GIS Cut Line= 4
      1277886.33      6945991.73      1278164.09      6945748.69
      1278559.06      6945740.01      1279330.84      6945423.50
#Sta/Elev= 30
  4336.8 2307.61  4458.8 2303.13  4487.3 2300.46  4515.8 2301.28  4565.1 2298.60
  4622.1 2299.60  4703.2 2295.33  4956.8 2292.11  4976.8 2289.22  4996.9 2279.25
  5008.3 2275.74  5010.1 2273.74  5022.1 2273.74  5023.9 2275.74  5026.9 2274.24
  5036.9 2276.31  5046.9 2281.33  5096.4 2287.70  5183.0 2286.20  5193.5 2283.13
  5198.9 2285.05  5204.6 2284.27  5215.4 2286.07  5258.7 2286.38  5269.5 2284.68
  5291.1 2286.81  5465.7 2288.37  5637.0 2287.32  5727.2 2291.24  5935.1 2289.96
#Mann=3,-1,0
  4336.8    0.05       0  5008.3    0.05       0  5023.9    0.05       0
Bank Sta=5008.3,5023.9
Exp/Cntr=0.3,0.1

Type RM Length L Ch R = 1,1108532,624,624,624
BEGIN DESCRIPTION:
Clear Fork Brazos Rv 396.0
END DESCRIPTION:
XS GIS Cut Line= 3
      1278081.71      6946735.04      1278852.38      6946155.63
      1279702.57      6944988.92
#Sta/Elev= 30
  4157.8 2343.86  4414.6 2336.38  4429.2 2334.91  4443.8 2330.35  4458.3 2328.65
  4479.2 2327.75  4493.7 2325.02  4643.7 2310.80  4793.6 2300.02  4914.4 2293.36
  4937.3 2288.20  4958.2 2279.58  4979.0 2276.70  4993.5 2270.70  4995.1 2268.70
  5005.1 2268.70  5006.6 2270.70  5014.4 2274.74  5029.0 2278.41  5079.0 2284.19
  5186.5 2281.14  5215.8 2283.04  5343.3 2284.47  5780.6 2285.06  5945.9 2289.15
  6002.3 2287.77  6073.4 2291.56  6213.7 2295.18  6308.5 2297.77  6565.6 2307.86
#Mann=5,-1,0
  4157.8    0.05       0  4993.5    0.03       0  5006.6    0.05       0
  6213.7    0.12       0  6308.5    0.05       0
#XS Ineff=2,0
       0                 5536.10    0.00 2313.59
Permanent Ineff=
       F       F
Bank Sta=4993.5,5006.6
Exp/Cntr=0.3,0.1

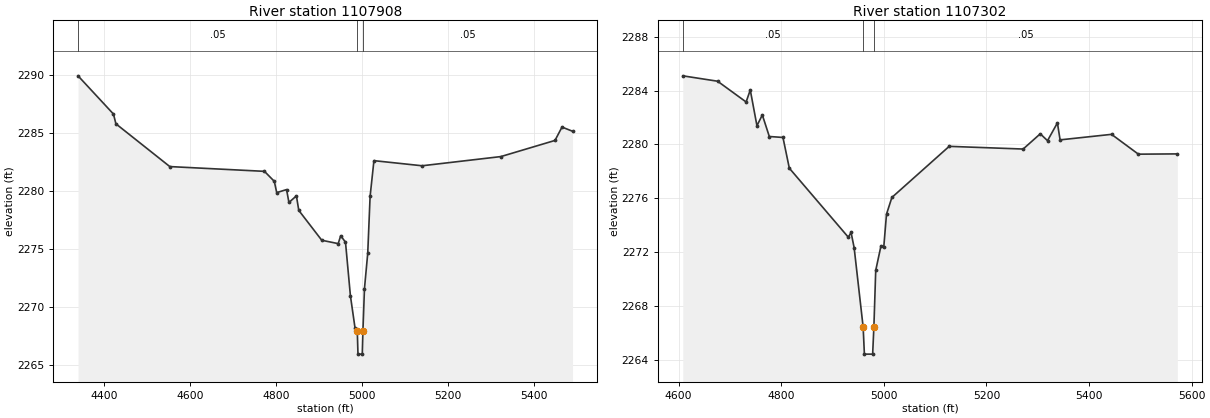
Type RM Length L Ch R = 1,1107908,606,606,606
BEGIN DESCRIPTION:
Mapping XS a7d6699c
END DESCRIPTION:
XS GIS Cut Line= 4
      1278849.88      6946634.07      1278980.07      6946395.39
      1279175.38      6945974.39      1279370.70      6945609.79
#Sta/Elev= 30
  4339.1 2289.91  4421.5 2286.62  4427.2 2285.78  4552.5 2282.10  4772.5 2281.69
  4795.4 2280.83  4801.0 2279.86  4823.9 2280.12  4829.4 2279.01  4846.8 2279.58
  4852.3 2278.33  4905.7 2275.76  4943.9 2275.47  4949.8 2276.15  4960.9 2275.59
  4972.3 2270.99  4982.9 2268.25  4988.3 2267.96  4989.9 2265.96  4999.9 2265.96
  5001.4 2267.96  5005.0 2271.60  5012.6 2274.64  5018.1 2279.54  5027.0 2282.61
  5139.0 2282.17  5322.0 2282.96  5447.9 2284.35  5464.2 2285.50  5488.7 2285.14
#Mann=3,-1,0
  4339.1    0.05       0  4988.3    0.03       0  5001.4    0.05       0
Bank Sta=4988.3,5001.4
Exp/Cntr=0.3,0.1

Type RM Length L Ch R = 1,1107302,255,255,255
BEGIN DESCRIPTION:
Mapping XS 88a2043e
END DESCRIPTION:
XS GIS Cut Line= 3
      1279058.19      6946955.29      1279218.78      6946464.84
      1279344.64      6946035.17
#Sta/Elev= 30
  4608.3 2285.09  4676.1 2284.69  4731.7 2283.15  4739.8 2284.04  4752.8 2281.39
  4763.3 2282.19  4776.9 2280.59  4803.5 2280.52  4815.9 2278.24  4930.9 2273.12
  4936.2 2273.48  4942.2 2272.35  4959.8 2266.45  4962.2 2264.45  4978.3 2264.45
  4980.7 2266.45  4984.3 2270.66  4994.6 2272.49  4999.9 2272.36  5005.3 2274.83
  5015.8 2276.07  5127.5 2279.86  5271.6 2279.66  5305.0 2280.79  5319.1 2280.28
  5338.4 2281.60  5343.6 2280.34  5443.9 2280.75  5496.2 2279.28  5572.1 2279.30
#Mann=3,-1,0
  4608.3    0.05       0  4959.8    0.05       0  4980.7    0.05       0
Bank Sta=4959.8,4980.7
Exp/Cntr=0.3,0.1