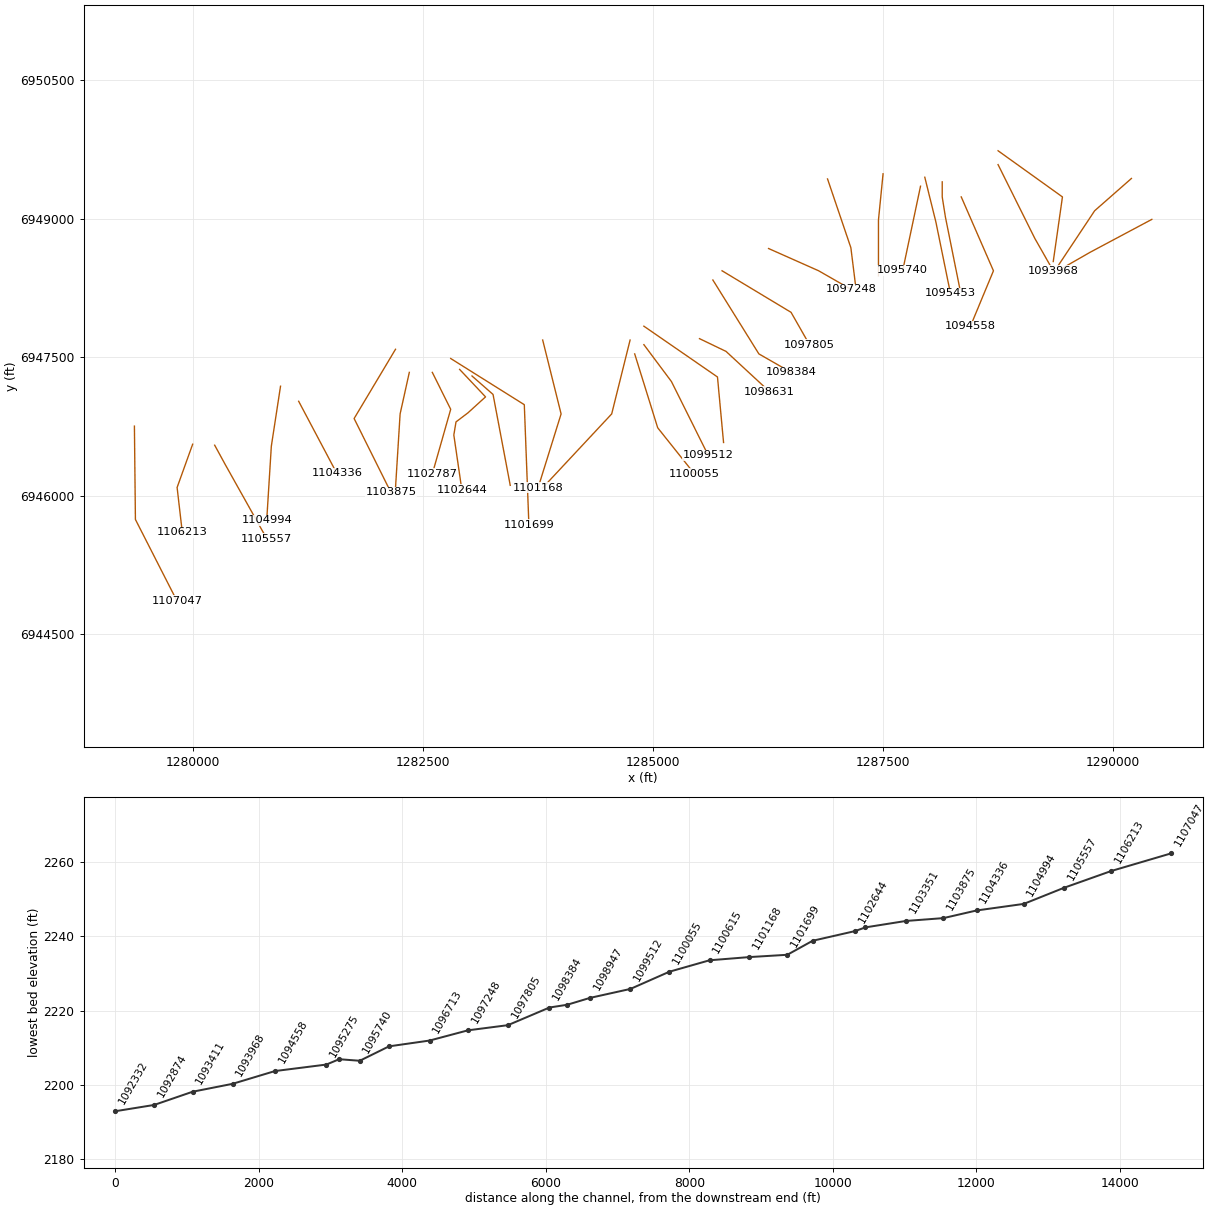
HEC-RAS study Clear Fork Brazos Rv.prj: Clear Fork Brazos Rv Base Level Engineering

--- Clear Fork Brazos Rv.g01 (geometry) --- (continued)

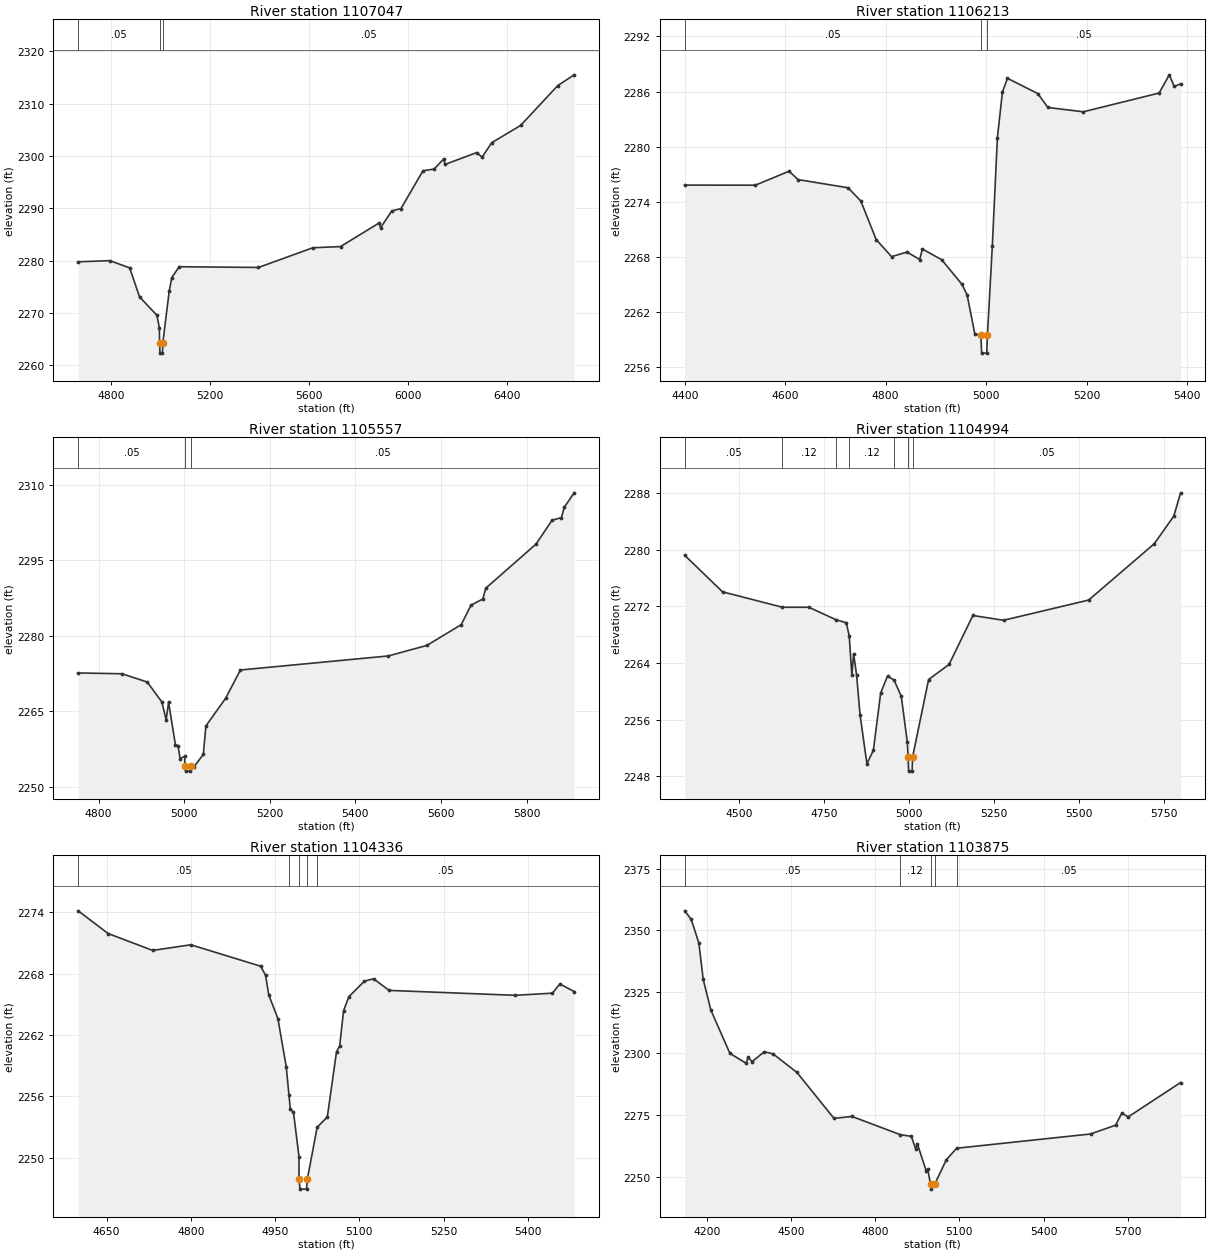
Type RM Length L Ch R = 1,1107047,834,834,834
BEGIN DESCRIPTION:
Clear Fork Brazos Rv 395.0
END DESCRIPTION:
XS GIS Cut Line= 3
      1279366.67      6946755.65      1279377.57      6945744.87
      1279829.42      6944862.36
#Sta/Elev= 30
  4667.6 2279.76  4795.3 2279.98  4875.3 2278.60  4915.3 2273.05  4985.3 2269.53
  4995.3 2267.14  4996.1 2264.30  4997.6 2262.30  5007.7 2262.30  5009.2 2264.30
  5035.3 2274.24  5045.3 2276.74  5075.3 2278.82  5395.3 2278.68  5615.3 2282.45
  5726.6 2282.67  5882.0 2287.17  5888.4 2286.28  5933.3 2289.47  5970.8 2289.94
  6059.6 2297.17  6104.1 2297.49  6142.9 2299.41  6148.5 2298.38  6276.1 2300.64
  6298.3 2299.77  6337.1 2302.53  6453.7 2305.83  6603.6 2313.45  6669.9 2315.51
#Mann=3,-1,0
  4667.6    0.05       0  4996.1    0.05       0  5009.2    0.05       0
Bank Sta=4996.1,5009.2
Exp/Cntr=0.3,0.1

Type RM Length L Ch R = 1,1106213,656,656,656
BEGIN DESCRIPTION:
Mapping XS 4fb2eb5c
END DESCRIPTION:
XS GIS Cut Line= 3
      1280000.03      6946560.31      1279830.76      6946091.57
      1279887.18      6945605.50
#Sta/Elev= 30
  4399.7 2275.83  4540.4 2275.82  4607.7 2277.34  4625.4 2276.43  4725.0 2275.54
  4750.4 2274.11  4781.1 2269.91  4811.7 2268.05  4842.4 2268.55  4867.8 2267.74
  4873.1 2268.88  4911.7 2267.71  4952.0 2265.04  4962.1 2263.91  4977.7 2259.61
  4989.6 2259.56  4991.1 2257.56  5001.2 2257.56  5002.7 2259.56  5012.4 2269.24
  5022.5 2280.98  5032.5 2285.95  5042.6 2287.44  5103.0 2285.78  5123.1 2284.27
  5193.6 2283.80  5344.6 2285.84  5364.8 2287.82  5374.8 2286.56  5387.4 2286.84
#Mann=3,-1,0
  4399.7    0.05       0  4989.6    0.05       0  5002.7    0.05       0
Bank Sta=4989.6,5002.7
Exp/Cntr=0.3,0.1

Type RM Length L Ch R = 1,1105557,563,563,563
BEGIN DESCRIPTION:
Clear Fork Brazos Rv 393.0
END DESCRIPTION:
XS GIS Cut Line= 3
      1280239.08      6946549.38      1280355.00      6946338.00
      1280805.02      6945537.96
#Sta/Elev= 30
  4752.2 2272.57  4854.4 2272.41  4913.4 2270.77  4947.7 2266.81  4957.7 2263.25
  4963.4 2266.74  4979.5 2258.21  4985.2 2258.15  4990.4 2255.54  5001.2 2256.02
  5001.5 2254.06  5003.0 2253.06  5013.2 2253.06  5014.7 2254.06  5022.9 2253.92
  5044.6 2256.40  5050.6 2262.04  5096.5 2267.51  5131.3 2273.16  5476.8 2275.95
  5566.9 2278.04  5647.3 2282.17  5670.2 2286.05  5697.9 2287.27  5704.6 2289.41
  5822.2 2298.19  5859.8 2302.94  5881.5 2303.43  5888.2 2305.52  5911.2 2308.37
#Mann=3,-1,0
  4752.2    0.05       0  5001.5    0.05       0  5014.7    0.05       0
Bank Sta=5001.5,5014.7
Exp/Cntr=0.3,0.1

Type RM Length L Ch R = 1,1104994,658,658,658
BEGIN DESCRIPTION:
Clear Fork Brazos Rv 392.0
END DESCRIPTION:
XS GIS Cut Line= 3
      1280955.00      6947187.98      1280855.00      6946538.00
      1280805.00      6945737.98
#Sta/Elev= 30
  4339.6 2279.19  4450.9 2274.03  4627.2 2271.85  4705.1 2271.85  4783.5 2270.12
  4815.1 2269.66  4823.7 2267.82  4831.5 2262.25  4836.6 2265.28  4845.5 2262.27
  4855.6 2256.65  4875.8 2249.74  4894.8 2251.65  4916.3 2259.75  4936.5 2262.15
  4955.7 2261.55  4977.0 2259.26  4994.7 2252.80  4997.0 2250.71  4998.5 2248.71
  5008.7 2248.71  5010.2 2250.71  5057.3 2261.64  5117.5 2263.78  5187.6 2270.69
  5277.8 2270.01  5528.3 2272.87  5721.1 2280.81  5778.7 2284.72  5798.8 2288.01
#Mann=7,-1,0
  4339.6    0.05       0  4627.2    0.12       0  4783.5    0.05       0
  4823.7    0.12       0  4955.7    0.05       0  4997.0    0.05       0
  5010.2    0.05       0
Bank Sta=4997,5010.2
Exp/Cntr=0.3,0.1

Type RM Length L Ch R = 1,1104336,461,461,461
BEGIN DESCRIPTION:
Mapping XS 0eb1d233
END DESCRIPTION:
XS GIS Cut Line= 2
      1281152.18      6947024.96      1281566.40      6946245.60
#Sta/Elev= 30
  4599.6 2274.15  4652.8 2271.93  4732.1 2270.28  4800.0 2270.83  4924.6 2268.73
  4933.1 2267.83  4938.7 2265.93  4955.0 2263.61  4969.9 2258.87  4974.7 2256.12
  4977.0 2254.80  4982.7 2254.45  4992.5 2250.12  4992.6 2247.94  4994.2 2246.94
  5005.9 2246.94  5007.5 2247.94  5024.8 2252.99  5042.9 2253.99  5059.3 2260.37
  5064.9 2260.95  5071.8 2264.37  5081.2 2265.75  5108.9 2267.27  5125.2 2267.51
  5152.8 2266.37  5377.6 2265.89  5443.5 2266.10  5456.8 2267.00  5482.2 2266.26
#Mann=5,-1,0
  4599.6    0.05       0  4974.7    0.12       0  4992.6    0.07       0
  5007.5    0.12       0  5024.8    0.05       0
Bank Sta=4992.6,5007.5
Exp/Cntr=0.3,0.1

Type RM Length L Ch R = 1,1103875,524,524,524
BEGIN DESCRIPTION:
Clear Fork Brazos Rv 390.0
END DESCRIPTION:
XS GIS Cut Line= 3
      1282205.02      6947588.03      1281755.00      6946838.00
      1282155.00      6946038.00
#Sta/Elev= 30
  4119.9 2357.96  4143.3 2354.49  4170.5 2344.87  4186.0 2330.13  4213.2 2317.64
  4281.3 2300.04  4339.6 2296.01  4345.4 2298.37  4360.9 2296.73  4403.7 2300.70
  4434.8 2299.87  4520.3 2292.31  4652.5 2273.63  4716.6 2274.42  4888.7 2267.03
  4928.5 2266.32  4944.0 2261.19  4949.9 2263.31  4981.0 2252.45  4986.8 2253.00
  4996.8 2246.89  4998.5 2244.89  5011.8 2246.89  5053.3 2256.83  5090.3 2261.51
  5567.6 2267.29  5657.0 2270.86  5679.4 2275.79  5701.7 2274.22  5889.0 2288.21
#Mann=5,-1,0
  4119.9    0.05       0  4888.7    0.12       0  4996.8    0.07       0
  5011.8    0.12       0  5090.3    0.05       0
Bank Sta=4996.8,5011.8
Exp/Cntr=0.3,0.1

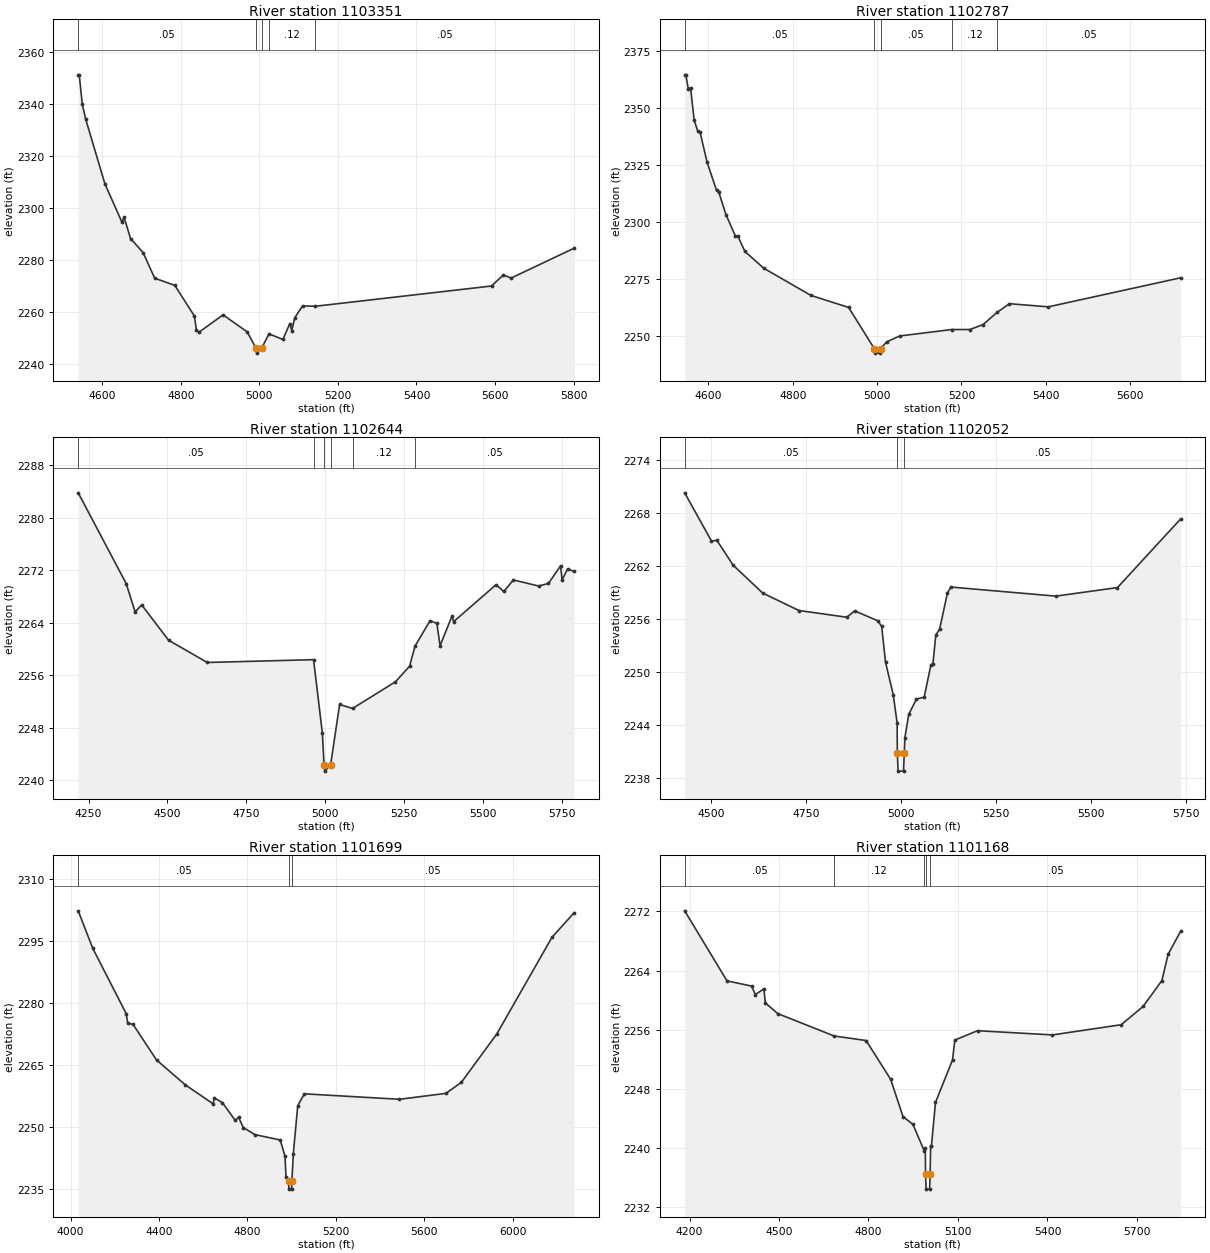
Type RM Length L Ch R = 1,1103351,564,564,564
BEGIN DESCRIPTION:
Clear Fork Brazos Rv 389.0
END DESCRIPTION:
XS GIS Cut Line= 3
      1282355.01      6947338.03      1282255.00      6946888.00
      1282205.00      6946087.96
#Sta/Elev= 30
  4538.9 2351.26  4541.5 2351.26  4549.2 2340.00  4558.1 2334.10  4606.8 2309.31
  4650.3 2294.50  4655.5 2296.49  4672.1 2288.24  4704.1 2282.83  4733.6 2272.97
  4784.8 2270.21  4834.7 2258.41  4839.8 2253.01  4846.2 2252.15  4907.7 2258.85
  4969.2 2252.29  4991.2 2246.12  4992.9 2244.12  5006.2 2246.12  5024.7 2251.54
  5060.0 2249.38  5077.6 2255.49  5082.6 2252.79  5090.1 2257.71  5110.1 2262.29
  5142.9 2262.17  5591.1 2269.96  5621.1 2274.20  5641.2 2273.03  5801.5 2284.53
#Mann=5,-1,0
  4538.9    0.05       0  4991.2    0.05       0  5006.2    0.05       0
  5024.7    0.12       0  5142.9    0.05       0
Bank Sta=4991.2,5006.2
Exp/Cntr=0.3,0.1

Type RM Length L Ch R = 1,1102787,143,143,143
BEGIN DESCRIPTION:
Clear Fork Brazos Rv 388.0
END DESCRIPTION:
XS GIS Cut Line= 3
      1282604.99      6947338.02      1282805.00      6946938.00
      1282604.99      6946237.95
#Sta/Elev= 30
  4544.0 2364.67  4546.8 2364.67  4552.4 2358.63  4558.0 2359.01  4566.4 2344.80
  4574.8 2340.05  4580.4 2339.52  4597.1 2326.28  4619.5 2313.90  4625.1 2312.99
  4641.9 2303.20  4664.2 2293.81  4669.8 2293.91  4686.6 2287.10  4731.3 2279.70
  4843.1 2267.75  4932.5 2262.47  4993.3 2244.39  4995.0 2242.39  5006.7 2242.39
  5008.4 2244.39  5022.4 2247.30  5053.6 2249.93  5176.9 2252.76  5220.0 2252.76
  5251.2 2254.96  5284.2 2260.27  5313.6 2264.11  5405.9 2262.73  5719.3 2275.49
#Mann=5,-1,0
  4544.0    0.05       0  4993.3    0.05       0  5008.4    0.05       0
  5176.9    0.12       0  5284.2    0.05       0
Bank Sta=4993.3,5008.4
Exp/Cntr=0.3,0.1

Type RM Length L Ch R = 1,1102644,592,592,592
BEGIN DESCRIPTION:
Mapping XS c2dba635
END DESCRIPTION:
XS GIS Cut Line= 6
      1282902.13      6947369.94      1283183.70      6947072.57
      1282991.60      6946898.89      1282862.65      6946801.52
      1282838.96      6946659.41      1282925.81      6946067.30
#Sta/Elev= 30
  4217.1 2283.82  4369.2 2269.99  4397.5 2265.68  4418.5 2266.73  4503.5 2261.36
  4626.3 2257.96  4963.4 2258.39  4991.4 2247.15  4996.5 2242.40  4998.8 2241.40
  5017.6 2242.40  5046.0 2251.56  5086.9 2250.95  5223.0 2255.01  5267.9 2257.40
  5285.2 2260.46  5332.7 2264.33  5354.4 2263.92  5364.5 2260.51  5402.5 2265.05
  5407.6 2264.19  5542.2 2269.82  5566.6 2268.78  5597.0 2270.54  5676.8 2269.62
  5708.1 2270.00  5746.6 2272.69  5751.6 2270.56  5768.8 2272.21  5789.7 2271.83
#Mann=6,-1,0
  4217.1    0.05       0  4963.4    0.12       0  4996.5    0.07       0
  5017.6    0.12       0  5086.9    0.12       0  5285.2    0.05       0
Bank Sta=4996.5,5017.6
Exp/Cntr=0.3,0.1

Type RM Length L Ch R = 1,1102052,353,353,353
BEGIN DESCRIPTION:
Mapping XS 017ee7ce
END DESCRIPTION:
XS GIS Cut Line= 3
      1283036.30      6947298.93      1283265.28      6947098.89
      1283452.14      6946114.62
#Sta/Elev= 30
  4430.9 2270.31  4501.5 2264.85  4515.7 2264.93  4558.4 2262.12  4636.2 2258.96
  4731.8 2256.98  4858.0 2256.22  4878.4 2256.94  4939.4 2255.82  4949.6 2255.19
  4959.8 2251.12  4980.1 2247.44  4990.3 2244.26  4990.9 2240.79  4992.9 2238.79
  5007.1 2238.79  5009.1 2240.79  5010.7 2242.57  5020.9 2245.21  5041.2 2246.95
  5061.6 2247.17  5079.4 2250.86  5084.5 2250.90  5092.1 2254.18  5102.3 2254.89
  5122.6 2258.93  5131.6 2259.64  5408.2 2258.61  5570.5 2259.58  5736.8 2267.35
#Mann=3,-1,0
  4430.9    0.05       0  4990.9    0.05       0  5009.1    0.05       0
Bank Sta=4990.9,5009.1
Exp/Cntr=0.3,0.1

Type RM Length L Ch R = 1,1101699,531,531,531
BEGIN DESCRIPTION:
Clear Fork Brazos Rv 386.0
END DESCRIPTION:
XS GIS Cut Line= 3
      1282804.97      6947488.02      1283605.00      6946988.00
      1283655.00      6945688.00
#Sta/Elev= 30
  4034.4 2302.33  4099.9 2293.30  4252.0 2277.41  4258.5 2275.09  4282.1 2274.91
  4388.8 2266.26  4519.7 2260.21  4644.7 2255.66  4650.6 2257.10  4687.2 2255.92
  4744.9 2251.65  4760.3 2252.39  4781.5 2249.92  4833.4 2248.22  4948.9 2246.90
  4970.2 2242.95  4974.9 2237.87  4986.4 2237.02  4988.0 2235.02  4999.8 2235.02
  5001.5 2237.02  5007.9 2243.60  5027.9 2255.20  5057.9 2258.07  5488.2 2256.75
  5698.4 2258.18  5768.4 2260.85  5928.5 2272.53  6178.7 2295.95  6278.8 2301.88
#Mann=3,-1,0
  4034.4    0.05       0  4986.4    0.05       0  5001.5    0.05       0
Bank Sta=4986.4,5001.5
Exp/Cntr=0.3,0.1

Type RM Length L Ch R = 1,1101168,553,553,553
BEGIN DESCRIPTION:
Clear Fork Brazos Rv 385.0
END DESCRIPTION:
XS GIS Cut Line= 3
      1283804.99      6947688.02      1284005.00      6946888.00
      1283755.00      6946088.00
#Sta/Elev= 30
  4183.7 2272.08  4325.5 2262.60  4407.9 2261.89  4420.8 2260.75  4449.1 2261.51
  4454.3 2259.61  4495.5 2258.17  4685.1 2255.13  4791.9 2254.52  4874.3 2249.27
  4915.6 2244.23  4949.1 2243.16  4987.7 2239.50  4990.3 2239.96  4991.4 2236.40
  4993.1 2234.40  5005.0 2234.40  5006.6 2236.40  5008.3 2240.24  5011.0 2240.24
  5024.6 2246.13  5081.7 2251.89  5089.5 2254.58  5165.5 2255.85  5416.9 2255.28
  5647.4 2256.66  5720.8 2259.14  5783.6 2262.63  5804.6 2266.20  5846.5 2269.31
#Mann=5,-1,0
  4183.7    0.05       0  4685.1    0.12       0  4987.7    0.05       0
  4991.4    0.05       0  5006.6    0.05       0
Bank Sta=4991.4,5006.6
Exp/Cntr=0.3,0.1

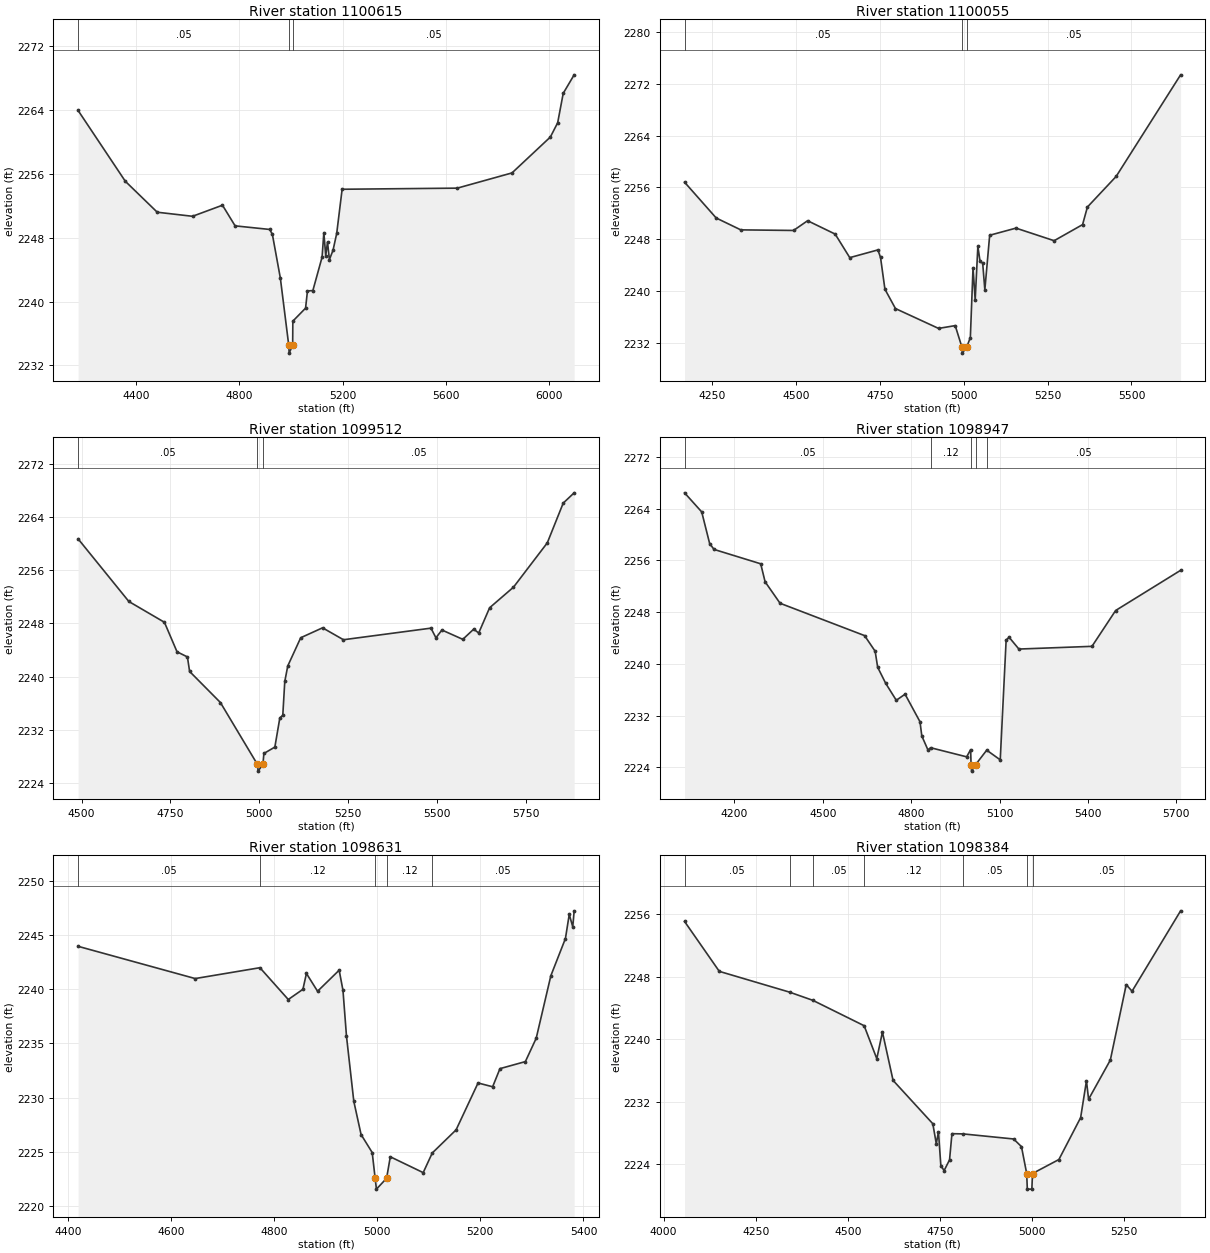
Type RM Length L Ch R = 1,1100615,560,560,560
BEGIN DESCRIPTION:
Clear Fork Brazos Rv 384.0
END DESCRIPTION:
XS GIS Cut Line= 3
      1284754.99      6947687.96      1284555.00      6946888.00
      1283804.97      6946087.97
#Sta/Elev= 30
  4175.2 2263.97  4358.1 2255.09  4481.8 2251.21  4618.4 2250.70  4734.4 2252.09
  4783.3 2249.50  4917.3 2249.05  4927.6 2248.44  4958.5 2242.96  4991.0 2234.54
  4992.7 2233.54  5006.2 2234.54  5006.9 2237.55  5056.2 2239.18  5063.5 2241.33
  5084.5 2241.39  5120.2 2245.58  5127.0 2248.65  5134.3 2245.76  5141.2 2247.48
  5148.5 2245.26  5162.7 2246.46  5176.8 2248.55  5197.8 2254.09  5643.8 2254.23
  5855.8 2256.14  6004.3 2260.64  6032.6 2262.43  6054.1 2266.12  6096.4 2268.44
#Mann=3,-1,0
  4175.2    0.05       0  4991.0    0.05       0  5006.2    0.05       0
Bank Sta=4991,5006.2
Exp/Cntr=0.3,0.1

Type RM Length L Ch R = 1,1100055,543,543,543
BEGIN DESCRIPTION:
Clear Fork Brazos Rv 383.0
END DESCRIPTION:
XS GIS Cut Line= 3
      1284805.00      6947538.01      1285055.00      6946738.00
      1285455.01      6946237.98
#Sta/Elev= 30
  4167.9 2256.81  4262.2 2251.29  4335.5 2249.46  4492.7 2249.37  4534.6 2250.87
  4616.8 2248.81  4660.3 2245.18  4744.1 2246.37  4752.0 2245.21  4765.1 2240.31
  4796.5 2237.33  4924.9 2234.27  4974.6 2234.70  4994.1 2231.46  4995.8 2230.46
  5009.3 2231.46  5019.7 2232.86  5027.7 2243.63  5034.1 2238.65  5042.1 2246.92
  5048.5 2244.65  5056.5 2244.32  5062.9 2240.22  5077.3 2248.63  5155.7 2249.73
  5269.4 2247.79  5354.2 2250.27  5368.6 2252.98  5454.3 2257.70  5646.4 2273.36
#Mann=3,-1,0
  4167.9    0.05       0  4994.1    0.05       0  5009.3    0.05       0
Bank Sta=4994.1,5009.3
Exp/Cntr=0.3,0.1

Type RM Length L Ch R = 1,1099512,565,565,565
BEGIN DESCRIPTION:
Clear Fork Brazos Rv 382.0
END DESCRIPTION:
XS GIS Cut Line= 3
      1284905.02      6947637.98      1285205.00      6947238.00
      1285605.00      6946438.00
#Sta/Elev= 30
  4490.3 2260.69  4633.0 2251.29  4733.0 2248.17  4768.4 2243.74  4797.6 2242.97
  4803.8 2240.79  4890.3 2236.13  4994.5 2226.83  4996.2 2225.83  5009.8 2226.83
  5012.6 2228.48  5043.4 2229.44  5057.4 2233.82  5065.7 2234.21  5071.3 2239.29
  5079.7 2241.62  5116.1 2245.85  5177.5 2247.34  5236.2 2245.55  5482.2 2247.29
  5496.2 2245.84  5513.0 2247.01  5571.7 2245.61  5602.4 2247.14  5616.4 2246.56
  5647.1 2250.35  5714.2 2253.44  5809.2 2260.09  5854.0 2266.06  5884.7 2267.60
#Mann=3,-1,0
  4490.3    0.05       0  4994.5    0.05       0  5009.8    0.05       0
Bank Sta=4994.5,5009.8
Exp/Cntr=0.3,0.1

Type RM Length L Ch R = 1,1098947,316,316,316
BEGIN DESCRIPTION:
Clear Fork Brazos Rv 381.0
END DESCRIPTION:
XS GIS Cut Line= 3
      1284905.00      6947838.00      1285705.00      6947288.00
      1285771.04      6946578.49
#Sta/Elev= 30
  4031.1 2266.43  4089.3 2263.48  4116.3 2258.58  4131.2 2257.68  4289.5 2255.46
  4304.4 2252.68  4355.2 2249.36  4642.0 2244.36  4677.9 2241.94  4686.4 2239.47
  4713.7 2236.98  4749.6 2234.36  4779.4 2235.30  4830.1 2231.04  4836.2 2228.85
  4857.1 2226.68  4866.0 2227.03  4988.4 2225.62  5001.9 2226.73  5003.4 2224.41
  5005.1 2223.41  5018.7 2224.41  5056.5 2226.65  5102.4 2225.15  5122.4 2243.67
  5132.5 2244.10  5165.7 2242.28  5413.7 2242.70  5494.0 2248.24  5714.5 2254.45
#Mann=5,-1,0
  4031.1    0.05       0  4866.0    0.12       0  5003.4    0.07       0
  5018.7    0.12       0  5056.5    0.05       0
Bank Sta=5003.4,5018.7
Exp/Cntr=0.3,0.1

Type RM Length L Ch R = 1,1098631,247,247,247
BEGIN DESCRIPTION:
Mapping XS 4cc9146f
END DESCRIPTION:
XS GIS Cut Line= 3
      1285509.54      6947703.14      1285797.98      6947565.06
      1286270.26      6947129.58
#Sta/Elev= 30
  4419.7 2243.94  4646.8 2240.97  4772.4 2241.97  4827.4 2239.04  4855.8 2239.98
  4862.6 2241.44  4884.2 2239.80  4926.1 2241.74  4933.5 2239.88  4940.3 2235.66
  4954.5 2229.66  4968.6 2226.60  4990.2 2224.94  4995.9 2222.57  4998.4 2221.57
  5018.1 2222.57  5025.3 2224.55  5089.1 2223.09  5106.7 2224.90  5152.9 2227.03
  5195.5 2231.35  5223.8 2231.00  5238.0 2232.67  5287.3 2233.32  5308.3 2235.47
  5336.7 2241.23  5365.0 2244.66  5372.4 2246.88  5379.2 2245.74  5381.9 2247.21
#Mann=5,-1,0
  4419.7    0.05       0  4772.4    0.12       0  4995.9    0.07       0
  5018.1    0.12       0  5106.7    0.05       0
Bank Sta=4995.9,5018.1
Exp/Cntr=0.3,0.1

Type RM Length L Ch R = 1,1098384,579,579,579
BEGIN DESCRIPTION:
Clear Fork Brazos Rv 380.0
END DESCRIPTION:
XS GIS Cut Line= 3
      1285655.02      6948337.96      1286155.00      6947538.00
      1286505.03      6947337.98
#Sta/Elev= 30
  4056.7 2255.10  4151.0 2248.71  4341.7 2246.05  4404.9 2245.00  4544.2 2241.75
  4578.5 2237.53  4593.8 2240.94  4622.7 2234.75  4730.6 2229.20  4740.0 2226.64
  4745.9 2228.17  4752.4 2223.82  4761.3 2223.21  4776.0 2224.58  4782.5 2227.93
  4812.9 2227.90  4949.9 2227.25  4971.2 2226.27  4985.4 2222.83  4987.1 2220.83
  4999.4 2220.83  5001.2 2222.83  5072.8 2224.62  5131.8 2229.98  5147.6 2234.69
  5153.4 2232.34  5212.4 2237.35  5255.6 2247.01  5271.4 2246.17  5403.2 2256.46
#Mann=7,-1,0
  4056.7    0.05       0  4341.7    0.12       0  4404.9    0.05       0
  4544.2    0.12       0  4812.9    0.05       0  4985.4    0.05       0
  5001.2    0.05       0
Bank Sta=4985.4,5001.2
Exp/Cntr=0.3,0.1

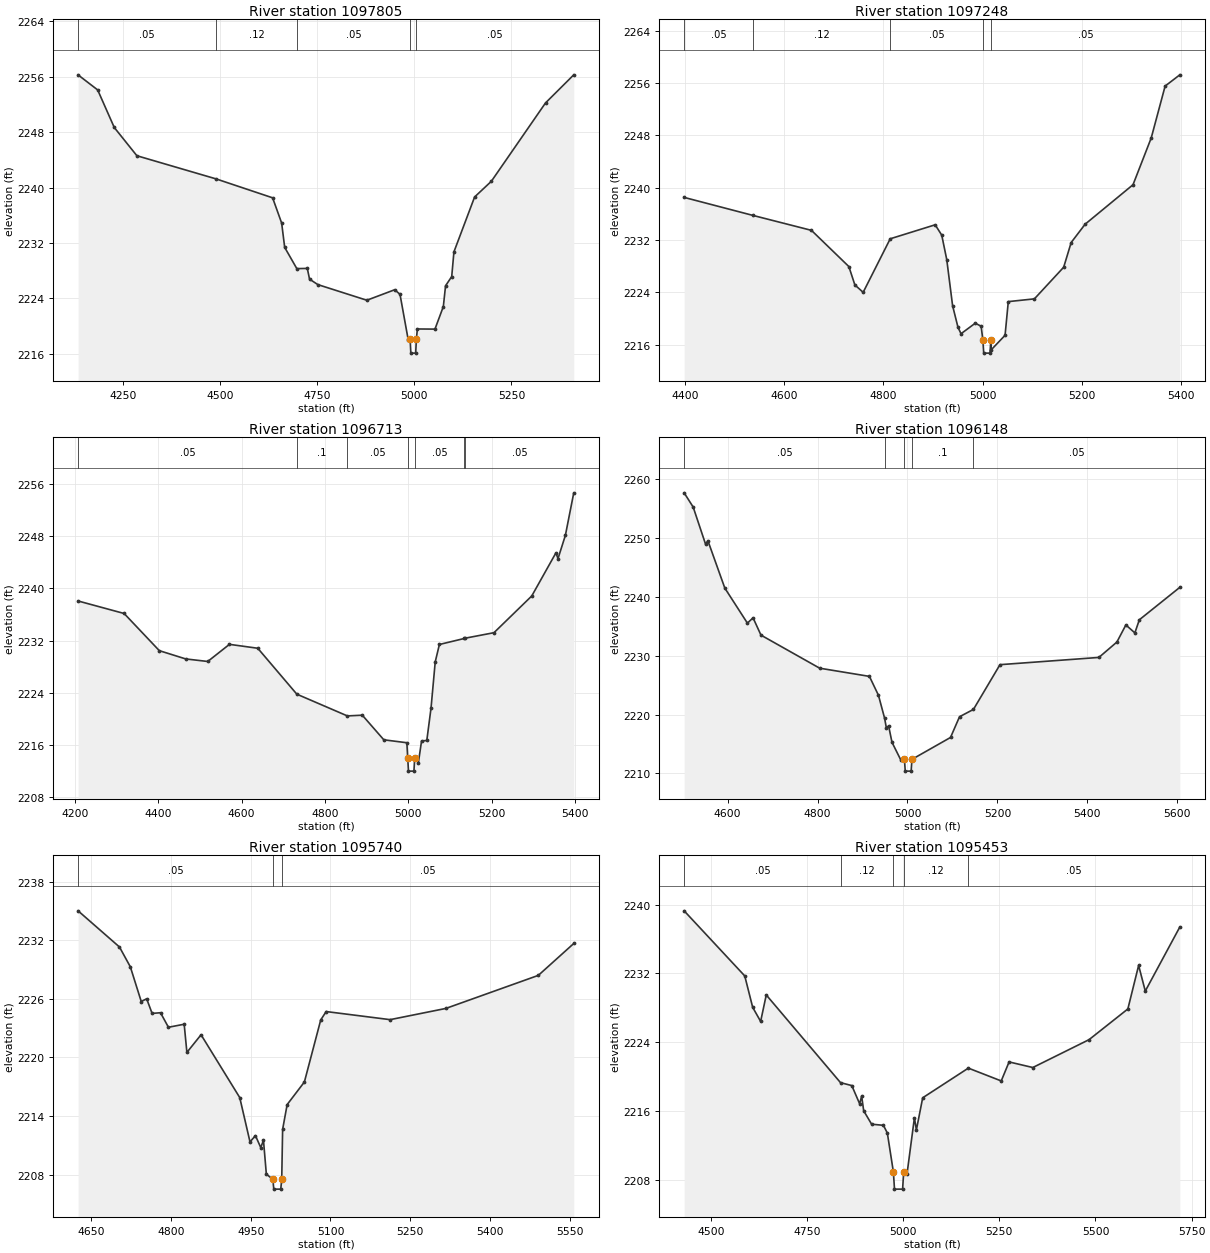
Type RM Length L Ch R = 1,1097805,557,557,557
BEGIN DESCRIPTION:
Clear Fork Brazos Rv 379.0
END DESCRIPTION:
XS GIS Cut Line= 3
      1285755.00      6948438.00      1286505.00      6947988.00
      1286705.02      6947637.96
#Sta/Elev= 30
  4133.0 2256.28  4183.5 2254.11  4226.3 2248.68  4284.6 2244.60  4488.4 2241.26
  4634.5 2238.52  4657.8 2234.87  4665.6 2231.36  4696.9 2228.29  4723.9 2228.32
  4729.7 2226.77  4751.1 2225.98  4877.4 2223.72  4949.3 2225.24  4962.9 2224.57
  4984.3 2217.93  4989.0 2218.08  4990.8 2216.08  5003.3 2216.08  5005.1 2218.08
  5007.6 2219.57  5053.0 2219.55  5074.6 2222.81  5080.3 2225.81  5096.2 2227.14
  5101.9 2230.71  5155.2 2238.64  5198.4 2240.91  5338.0 2252.23  5410.8 2256.29
#Mann=5,-1,0
  4133.0    0.05       0  4488.4    0.12       0  4696.9    0.05       0
  4989.0    0.05       0  5005.1    0.05       0
Bank Sta=4989,5005.1
Exp/Cntr=0.3,0.1

Type RM Length L Ch R = 1,1097248,535,535,535
BEGIN DESCRIPTION:
Clear Fork Brazos Rv 378.0
END DESCRIPTION:
XS GIS Cut Line= 3
      1286260.49      6948679.20      1286805.00      6948438.00
      1287155.04      6948237.98
#Sta/Elev= 30
  4398.8 2238.51  4537.7 2235.75  4655.3 2233.47  4730.7 2227.93  4742.8 2225.12
  4759.5 2223.99  4814.0 2232.18  4904.6 2234.32  4917.8 2232.74  4927.9 2229.00
  4939.7 2221.94  4950.6 2218.62  4956.7 2217.66  4985.4 2219.27  4997.2 2218.80
  5000.7 2216.69  5002.4 2214.69  5015.0 2214.69  5016.8 2216.69  5017.4 2215.19
  5045.4 2217.42  5051.9 2222.57  5104.5 2222.99  5163.5 2227.83  5178.6 2231.61
  5206.7 2234.41  5303.2 2240.45  5339.9 2247.61  5367.9 2255.54  5397.5 2257.26
#Mann=5,-1,0
  4398.8    0.05       0  4537.7    0.12       0  4814.0    0.05       0
  5000.7    0.05       0  5016.8    0.05       0
Bank Sta=5000.7,5016.8
Exp/Cntr=0.3,0.1

Type RM Length L Ch R = 1,1096713,565,565,565
BEGIN DESCRIPTION:
Clear Fork Brazos Rv 377.0
END DESCRIPTION:
XS GIS Cut Line= 3
      1286901.37      6949432.60      1287155.00      6948688.00
      1287205.00      6948288.02
#Sta/Elev= 30
  4207.7 2238.07  4318.2 2236.15  4402.7 2230.44  4466.1 2229.17  4518.9 2228.78
  4571.0 2231.41  4639.0 2230.81  4732.7 2223.76  4854.0 2220.42  4889.9 2220.53
  4941.5 2216.75  4996.8 2216.30  4998.9 2213.94  5000.7 2211.94  5013.8 2211.94
  5015.6 2213.94  5024.5 2213.26  5032.1 2216.57  5044.7 2216.65  5054.8 2221.60
  5064.9 2228.72  5074.9 2231.39  5135.1 2232.32  5136.3 2232.35  5205.9 2233.20
  5296.6 2238.84  5354.6 2245.46  5359.6 2244.58  5377.3 2248.15  5397.4 2254.68
#Mann=7,-1,0
  4207.7    0.05       0  4732.7     0.1       0  4854.0    0.05       0
  4998.9    0.05       0  5015.6    0.05       0  5135.1    0.12       0
  5136.3    0.05       0
Bank Sta=4998.9,5015.6
Exp/Cntr=0.3,0.1

Type RM Length L Ch R = 1,1096148,408,408,408
BEGIN DESCRIPTION:
Clear Fork Brazos Rv 376.0
END DESCRIPTION:
XS GIS Cut Line= 3
      1287505.00      6949488.01      1287455.00      6948988.00
      1287455.00      6948388.00
#Sta/Elev= 30
  4503.3 2257.67  4523.4 2255.25  4551.0 2248.93  4556.1 2249.54  4593.8 2241.48
  4644.0 2235.53  4656.6 2236.43  4674.2 2233.49  4804.8 2227.87  4915.4 2226.48
  4935.5 2223.27  4949.1 2219.39  4953.0 2217.76  4958.1 2218.06  4965.6 2215.28
  4985.7 2212.20  4993.3 2212.38  4995.1 2210.38  5008.2 2210.38  5010.0 2212.38
  5095.8 2216.10  5115.8 2219.62  5146.8 2220.87  5205.8 2228.47  5425.8 2229.70
  5465.8 2232.31  5485.8 2235.22  5505.8 2233.87  5515.8 2236.10  5605.8 2241.61
#Mann=5,-1,0
  4503.3    0.05       0  4949.1     0.1       0  4993.3    0.07       0
  5010.0     0.1       0  5146.8    0.05       0
Bank Sta=4993.3,5010
Exp/Cntr=0.3,0.1

Type RM Length L Ch R = 1,1095740,287,287,287
BEGIN DESCRIPTION:
Mapping XS 21316f03
END DESCRIPTION:
XS GIS Cut Line= 2
      1287912.23      6949354.07      1287718.94      6948442.85
#Sta/Elev= 30
  4625.7 2235.04  4703.5 2231.33  4723.9 2229.30  4744.4 2225.74  4754.6 2226.02
  4764.8 2224.52  4780.6 2224.59  4795.5 2223.10  4825.1 2223.41  4830.2 2220.52
  4856.8 2222.33  4929.5 2215.89  4948.8 2211.34  4959.0 2211.99  4969.0 2210.76
  4974.1 2211.51  4979.5 2208.04  4991.7 2207.50  4993.5 2206.50  5006.6 2206.50
  5008.4 2207.50  5010.1 2212.63  5018.6 2215.17  5051.0 2217.49  5081.7 2223.85
  5091.9 2224.71  5212.1 2223.88  5316.8 2225.03  5490.6 2228.42  5557.2 2231.69
#Mann=3,-1,0
  4625.7    0.05       0  4991.7    0.05       0  5008.4    0.05       0
Bank Sta=4991.7,5008.4
Exp/Cntr=0.3,0.1

Type RM Length L Ch R = 1,1095453,178,178,178
BEGIN DESCRIPTION:
Mapping XS f374758d
END DESCRIPTION:
XS GIS Cut Line= 3
      1287958.67      6949450.98      1288079.72      6948964.17
      1288237.61      6948193.10
#Sta/Elev= 30
  4430.6 2239.28  4588.2 2231.71  4608.8 2228.06  4629.5 2226.42  4644.1 2229.50
  4837.2 2219.30  4866.5 2218.96  4886.9 2216.84  4892.1 2217.74  4897.4 2216.03
  4918.0 2214.47  4948.7 2214.34  4958.9 2213.44  4974.6 2208.92  4977.5 2206.92
  4998.6 2206.92  5001.4 2208.92  5010.0 2208.67  5029.3 2215.22  5034.4 2213.80
  5050.8 2217.54  5169.5 2220.99  5255.0 2219.50  5275.4 2221.71  5337.1 2221.06
  5483.3 2224.30  5584.2 2227.87  5612.2 2232.93  5629.5 2229.95  5719.3 2237.40
#Mann=5,-1,0
  4430.6    0.05       0  4837.2    0.12       0  4974.6    0.07       0
  5001.4    0.12       0  5169.5    0.05       0
Bank Sta=4974.6,5001.4
Exp/Cntr=0.3,0.1

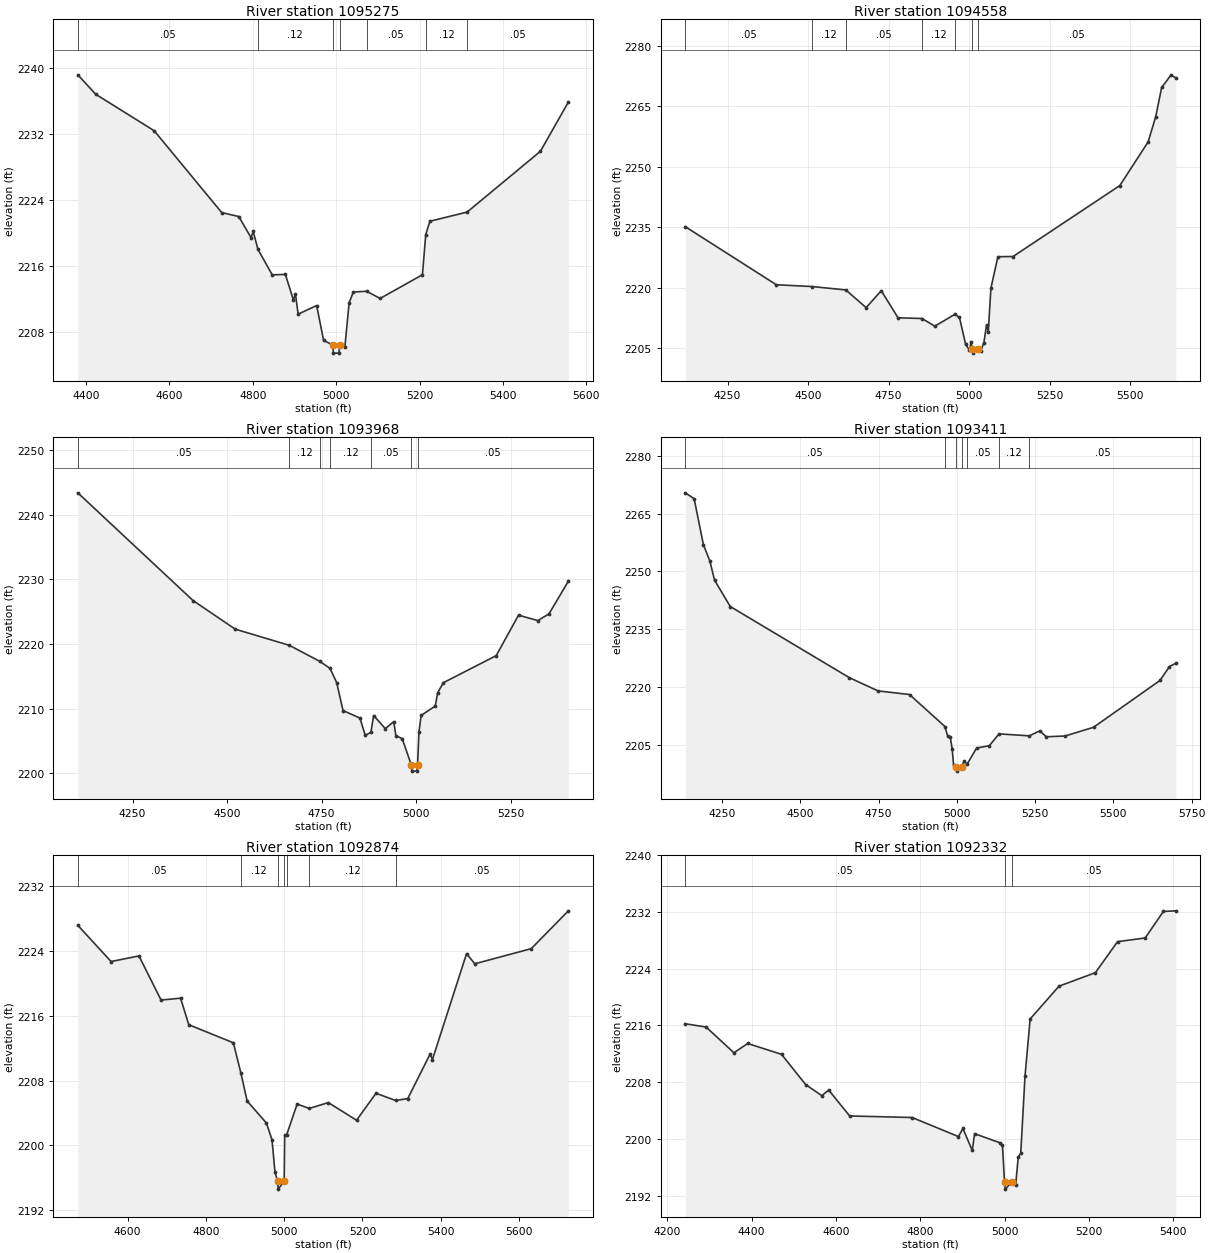
Type RM Length L Ch R = 1,1095275,717,717,717
BEGIN DESCRIPTION:
Mapping XS 47273c4f
END DESCRIPTION:
XS GIS Cut Line= 4
      1288148.14      6949401.05      1288148.14      6949237.85
      1288182.35      6949022.06      1288339.88      6948242.30
#Sta/Elev= 30
  4380.0 2239.18  4423.1 2236.82  4563.3 2232.41  4725.3 2222.50  4766.3 2222.02
  4795.8 2219.46  4800.9 2220.21  4812.3 2218.04  4846.6 2214.96  4878.1 2215.01
  4897.3 2211.93  4902.4 2212.61  4908.7 2210.20  4953.2 2211.24  4969.9 2207.01
  4991.6 2206.48  4993.5 2205.48  5006.6 2205.48  5008.4 2206.48  5020.9 2206.21
  5031.1 2211.59  5041.3 2212.88  5073.1 2212.97  5105.5 2212.10  5207.0 2214.97
  5215.0 2219.83  5224.9 2221.45  5314.3 2222.56  5490.2 2229.92  5557.2 2235.88
#Mann=7,-1,0
  4380.0    0.05       0  4812.3    0.12       0  4991.6    0.07       0
  5008.4    0.12       0  5073.1    0.05       0  5215.0    0.12       0
  5314.3    0.05       0
Bank Sta=4991.6,5008.4
Exp/Cntr=0.3,0.1

Type RM Length L Ch R = 1,1094558,590,590,590
BEGIN DESCRIPTION:
Clear Fork Brazos Rv 373.0
END DESCRIPTION:
XS GIS Cut Line= 3
      1288355.00      6949238.00      1288705.00      6948438.00
      1288455.01      6947838.02
#Sta/Elev= 30
  4118.6 2235.14  4401.2 2220.72  4511.4 2220.27  4617.0 2219.43  4680.3 2215.03
  4727.1 2219.24  4779.4 2212.50  4853.5 2212.33  4893.6 2210.43  4956.1 2213.39
  4970.0 2212.58  4989.1 2205.95  5001.0 2204.45  5006.4 2206.51  5009.4 2204.73
  5011.3 2203.73  5026.3 2204.73  5035.7 2204.23  5046.0 2206.36  5054.1 2210.77
  5059.5 2209.10  5067.7 2219.87  5089.3 2227.68  5136.4 2227.73  5467.9 2245.35
  5555.7 2256.17  5579.5 2262.48  5597.9 2269.72  5627.2 2272.86  5641.8 2272.07
#Mann=7,-1,0
  4118.6    0.05       0  4511.4    0.12       0  4617.0    0.05       0
  4853.5    0.12       0  4956.1    0.05       0  5009.4    0.05       0
  5026.3    0.05       0
Bank Sta=5009.4,5026.3
Exp/Cntr=0.3,0.1

Type RM Length L Ch R = 1,1093968,557,557,557
BEGIN DESCRIPTION:
Clear Fork Brazos Rv 372.0
END DESCRIPTION:
XS GIS Cut Line= 3
      1288754.99      6949588.02      1289155.00      6948788.00
      1289355.02      6948437.96
#Sta/Elev= 30
  4105.3 2243.43  4410.0 2226.74  4521.8 2222.30  4664.7 2219.80  4745.1 2217.32
  4772.7 2216.21  4790.1 2214.01  4806.9 2209.69  4851.6 2208.52  4865.6 2205.85
  4880.6 2206.30  4887.9 2208.92  4918.7 2206.89  4941.0 2207.96  4946.6 2205.80
  4963.4 2205.34  4987.3 2201.30  4989.1 2200.30  5002.3 2200.30  5004.1 2201.30
  5007.7 2206.31  5013.4 2208.93  5050.9 2210.39  5057.3 2212.46  5072.5 2214.01
  5212.1 2218.20  5271.1 2224.47  5322.2 2223.63  5351.7 2224.67  5402.9 2229.73
#Mann=7,-1,0
  4105.3    0.05       0  4664.7    0.12       0  4745.1    0.05       0
  4772.7    0.12       0  4880.6    0.05       0  4987.3    0.05       0
  5004.1    0.05       0
Bank Sta=4987.3,5004.1
Exp/Cntr=0.3,0.1

Type RM Length L Ch R = 1,1093411,537,537,537
BEGIN DESCRIPTION:
Clear Fork Brazos Rv 371.0
END DESCRIPTION:
XS GIS Cut Line= 3
      1288754.98      6949738.01      1289455.00      6949238.00
      1289354.99      6948537.96
#Sta/Elev= 30
  4132.0 2270.42  4160.3 2268.90  4189.8 2256.98  4210.7 2252.68  4225.4 2247.75
  4275.8 2240.90  4655.5 2222.47  4747.7 2219.00  4848.5 2218.06  4961.9 2209.73
  4970.1 2207.35  4978.7 2206.99  4984.9 2203.95  4989.2 2199.80  4997.8 2199.17
  4999.6 2198.17  5014.7 2199.17  5022.6 2200.73  5032.7 2200.00  5063.0 2204.17
  5103.4 2204.76  5134.5 2207.84  5231.3 2207.33  5265.0 2208.64  5285.2 2207.09
  5345.8 2207.29  5436.7 2209.56  5648.9 2221.71  5679.2 2225.33  5699.4 2226.16
#Mann=7,-1,0
  4132.0    0.05       0  4961.9    0.12       0  4997.8    0.07       0
  5014.7    0.12       0  5032.7    0.05       0  5134.5    0.12       0
  5231.3    0.05       0
Bank Sta=4997.8,5014.7
Exp/Cntr=0.3,0.1

Type RM Length L Ch R = 1,1092874,542,542,542
BEGIN DESCRIPTION:
Clear Fork Brazos Rv 370.0
END DESCRIPTION:
XS GIS Cut Line= 3
      1290204.99      6949437.99      1289805.00      6949088.00
      1289405.00      6948488.01
#Sta/Elev= 30
  4473.1 2227.13  4558.0 2222.67  4629.2 2223.36  4685.7 2217.92  4735.5 2218.15
  4756.4 2214.88  4870.3 2212.65  4889.3 2208.97  4905.4 2205.48  4954.8 2202.75
  4969.0 2200.68  4976.6 2196.70  4983.1 2195.61  4985.0 2194.61  5000.1 2195.61
  5001.3 2201.26  5006.1 2201.26  5033.1 2205.09  5064.5 2204.56  5112.8 2205.28
  5184.9 2203.10  5234.5 2206.43  5284.4 2205.54  5315.6 2205.77  5372.7 2211.26
  5378.7 2210.59  5465.8 2223.64  5486.8 2222.39  5631.1 2224.26  5725.7 2228.92
#Mann=7,-1,0
  4473.1    0.05       0  4889.3    0.12       0  4983.1    0.07       0
  5000.1    0.12       0  5006.1    0.05       0  5064.5    0.12       0
  5284.4    0.05       0
Bank Sta=4983.1,5000.1
Exp/Cntr=0.3,0.1

Type RM Length L Ch R = 1,1092332,521,521,521
BEGIN DESCRIPTION:
Clear Fork Brazos Rv 369.0
END DESCRIPTION:
XS GIS Cut Line= 3
      1290426.63      6948994.60      1289755.00      6948638.00
      1289405.03      6948438.02
#Sta/Elev= 30
  4242.7 2216.24  4292.1 2215.78  4358.1 2212.15  4390.7 2213.46  4471.0 2211.93
  4528.3 2207.66  4566.6 2206.10  4582.9 2206.89  4632.6 2203.24  4780.8 2203.02
  4890.7 2200.33  4901.2 2201.48  4923.3 2198.38  4929.0 2200.74  4989.3 2199.45
  4995.0 2199.16  4999.9 2193.92  5001.8 2192.92  5016.9 2193.92  5026.2 2193.45
  5032.6 2197.51  5038.4 2197.95  5048.5 2208.85  5060.7 2216.92  5129.1 2221.54
  5215.5 2223.45  5268.0 2227.82  5333.5 2228.34  5376.7 2232.08  5406.2 2232.17
#Mann=3,-1,0
  4242.7    0.05       0  4999.9    0.05       0  5016.9    0.05       0
Bank Sta=4999.9,5016.9
Exp/Cntr=0.3,0.1