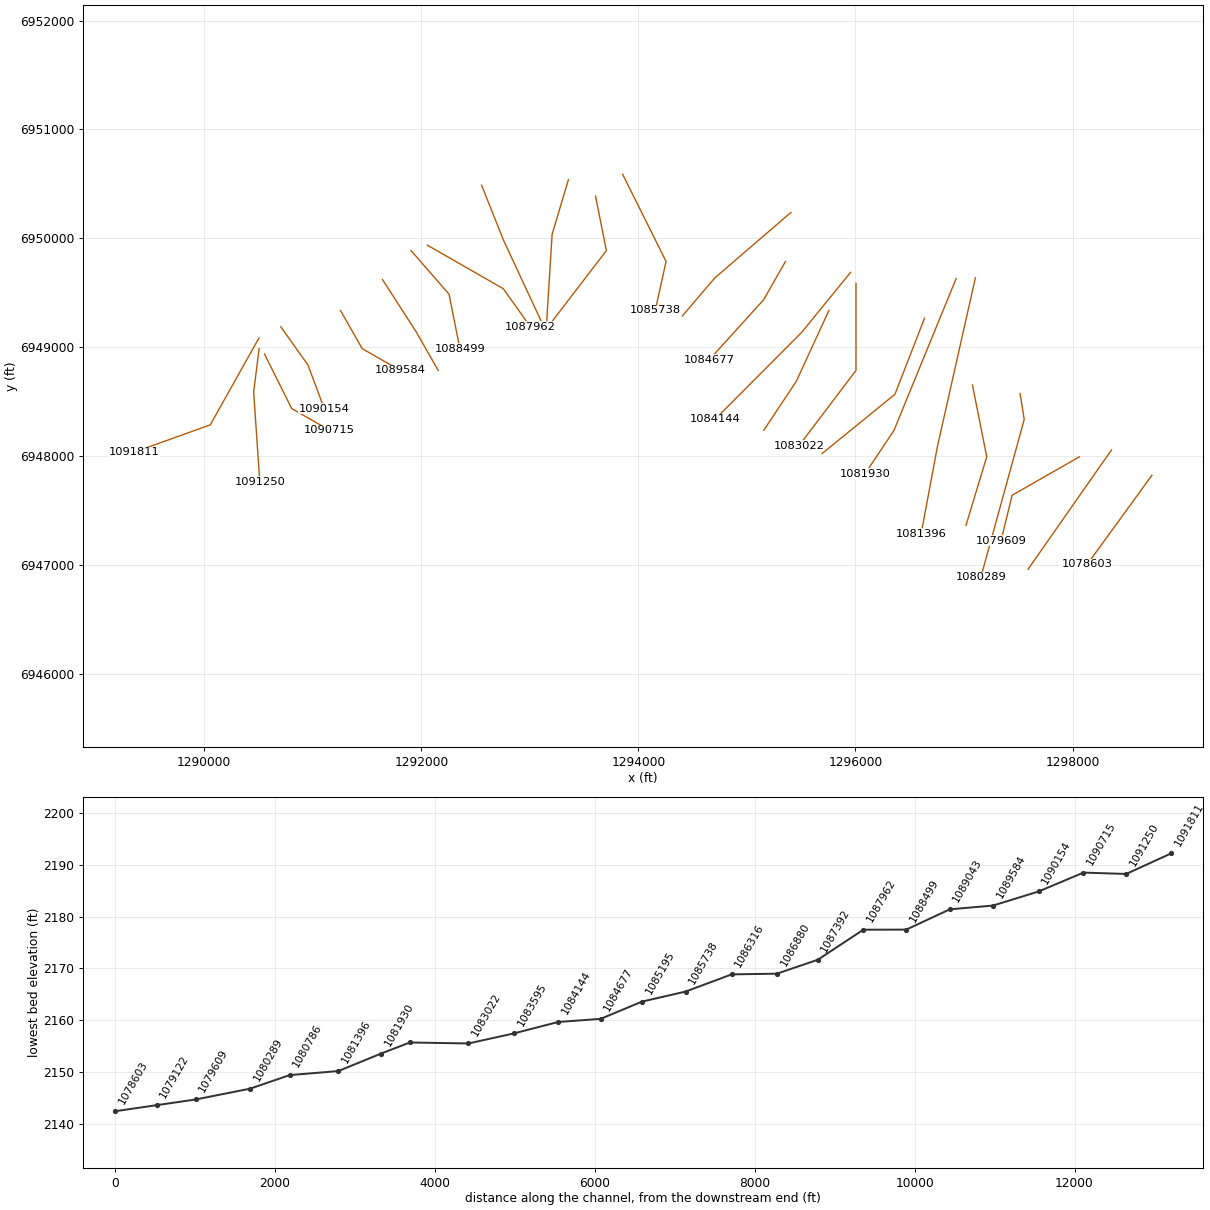
HEC-RAS study Clear Fork Brazos Rv.prj: Clear Fork Brazos Rv Base Level Engineering

--- Clear Fork Brazos Rv.g01 (geometry) --- (continued)

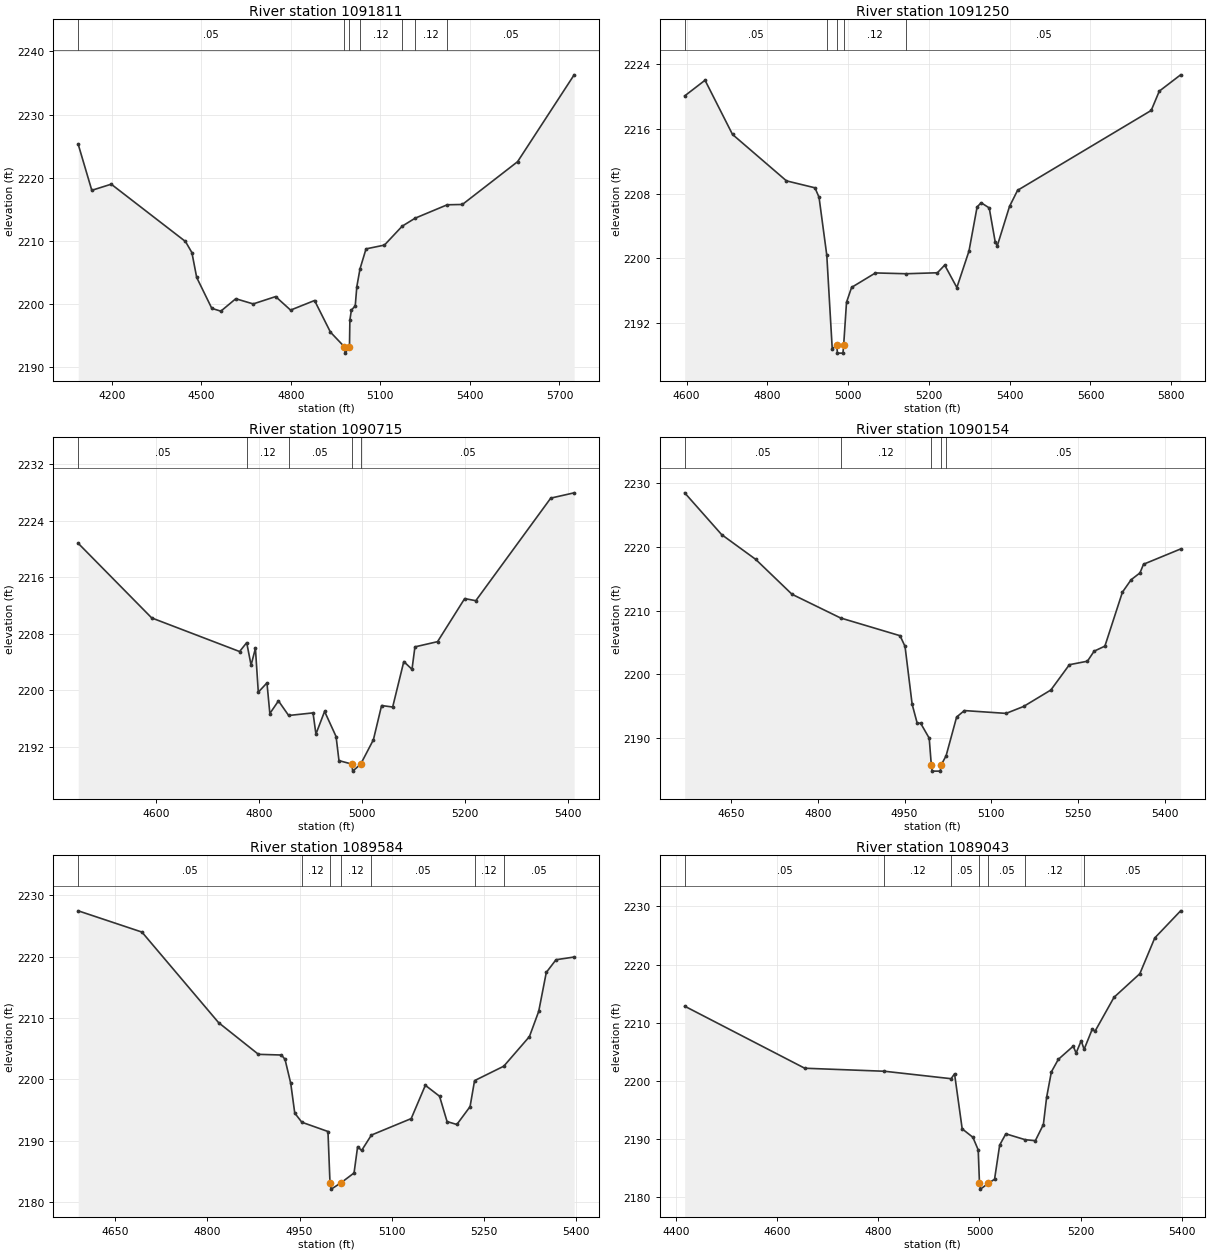
Type RM Length L Ch R = 1,1091811,561,561,561
BEGIN DESCRIPTION:
Clear Fork Brazos Rv 368.0
END DESCRIPTION:
XS GIS Cut Line= 3
      1290504.98      6949087.97      1290055.00      6948288.00
      1289355.05      6948038.02
#Sta/Elev= 30
  4088.0 2225.28  4133.5 2218.00  4198.6 2218.97  4447.2 2209.90  4468.8 2208.14
  4484.8 2204.21  4535.4 2199.32  4565.7 2198.87  4615.7 2200.84  4674.1 2200.02
  4749.3 2201.18  4799.3 2199.04  4879.6 2200.56  4932.9 2195.55  4979.6 2193.23
  4981.5 2192.23  4996.6 2193.23  4997.9 2197.46  5003.0 2199.04  5015.9 2199.71
  5021.2 2202.76  5031.9 2205.58  5052.0 2208.73  5113.6 2209.33  5173.3 2212.33
  5216.5 2213.59  5324.0 2215.71  5374.8 2215.76  5559.6 2222.53  5749.1 2236.28
#Mann=7,-1,0
  4088.0    0.05       0  4979.6    0.05       0  4996.6    0.05       0
  5031.9    0.12       0  5173.3    0.05       0  5216.5    0.12       0
  5324.0    0.05       0
Bank Sta=4979.6,4996.6
Exp/Cntr=0.3,0.1

Type RM Length L Ch R = 1,1091250,535,535,535
BEGIN DESCRIPTION:
Clear Fork Brazos Rv 367.0
END DESCRIPTION:
XS GIS Cut Line= 3
      1290505.00      6948988.01      1290455.00      6948588.00
      1290511.38      6947765.36
#Sta/Elev= 30
  4595.4 2220.11  4645.8 2222.05  4713.8 2215.34  4847.4 2209.59  4917.9 2208.73
  4928.0 2207.56  4947.2 2200.38  4960.7 2188.76  4971.7 2189.26  4973.6 2188.26
  4987.2 2188.26  4989.0 2189.26  4996.0 2194.55  5008.6 2196.40  5067.7 2198.19
  5143.6 2198.09  5221.0 2198.21  5239.1 2199.16  5269.2 2196.38  5299.2 2200.90
  5319.3 2206.36  5329.3 2206.88  5349.3 2206.24  5364.3 2201.98  5369.4 2201.57
  5399.5 2206.42  5419.5 2208.42  5750.3 2218.31  5770.3 2220.70  5823.1 2222.72
#Mann=5,-1,0
  4595.4    0.05       0  4947.2    0.12       0  4971.7    0.07       0
  4989.0    0.12       0  5143.6    0.05       0
Bank Sta=4971.7,4989
Exp/Cntr=0.3,0.1

Type RM Length L Ch R = 1,1090715,561,561,561
BEGIN DESCRIPTION:
Clear Fork Brazos Rv 366.0
END DESCRIPTION:
XS GIS Cut Line= 3
      1290554.99      6948938.02      1290805.00      6948438.00
      1291155.04      6948237.98
#Sta/Elev= 30
  4449.5 2220.79  4592.1 2210.22  4762.6 2205.46  4776.4 2206.72  4784.9 2203.53
  4793.3 2205.91  4798.9 2199.70  4815.7 2201.02  4821.3 2196.68  4838.0 2198.47
  4857.8 2196.40  4905.1 2196.77  4910.7 2193.77  4927.5 2196.98  4949.8 2193.42
  4955.4 2190.01  4980.2 2189.52  4982.1 2188.52  4997.6 2189.52  5022.2 2192.96
  5038.1 2197.81  5059.6 2197.60  5081.2 2204.04  5097.1 2202.94  5102.8 2206.12
  5146.7 2206.86  5199.3 2212.96  5220.9 2212.66  5366.3 2227.19  5411.7 2227.94
#Mann=5,-1,0
  4449.5    0.05       0  4776.4    0.12       0  4857.8    0.05       0
  4980.2    0.05       0  4997.6    0.05       0
Bank Sta=4980.2,4997.6
Exp/Cntr=0.3,0.1

Type RM Length L Ch R = 1,1090154,570,570,570
BEGIN DESCRIPTION:
Clear Fork Brazos Rv 365.0
END DESCRIPTION:
XS GIS Cut Line= 3
      1290705.02      6949187.97      1290955.00      6948838.00
      1291105.01      6948437.98
#Sta/Elev= 30
  4570.0 2228.44  4633.9 2221.90  4692.8 2218.02  4755.5 2212.56  4839.4 2208.85
  4942.3 2206.07  4950.9 2204.40  4963.2 2195.34  4971.8 2192.42  4978.0 2192.35
  4992.7 2190.03  4996.3 2185.87  4998.1 2184.87  5011.8 2184.87  5013.6 2185.87
  5021.9 2187.27  5040.1 2193.34  5053.5 2194.35  5125.6 2193.91  5155.8 2194.99
  5203.0 2197.57  5235.0 2201.53  5266.2 2202.08  5277.8 2203.65  5296.4 2204.44
  5326.7 2212.89  5341.8 2214.84  5357.0 2215.90  5363.2 2217.26  5427.3 2219.65
#Mann=5,-1,0
  4570.0    0.05       0  4839.4    0.12       0  4996.3    0.07       0
  5013.6    0.12       0  5021.9    0.05       0
Bank Sta=4996.3,5013.6
Exp/Cntr=0.3,0.1

Type RM Length L Ch R = 1,1089584,541,541,541
BEGIN DESCRIPTION:
Clear Fork Brazos Rv 364.0
END DESCRIPTION:
XS GIS Cut Line= 3
      1291255.01      6949337.99      1291455.00      6948988.00
      1291804.99      6948788.01
#Sta/Elev= 30
  4590.1 2227.45  4693.7 2223.99  4818.3 2209.25  4883.1 2204.09  4920.5 2203.98
  4926.3 2203.27  4935.6 2199.36  4942.1 2194.53  4953.6 2193.04  4996.1 2191.53
  4999.4 2183.15  5001.3 2182.15  5016.9 2183.15  5038.5 2184.78  5044.3 2189.06
  5050.8 2188.44  5066.7 2190.95  5131.4 2193.63  5154.4 2199.05  5177.5 2197.27
  5189.7 2193.15  5205.6 2192.67  5227.1 2195.58  5234.4 2199.81  5281.9 2202.16
  5323.6 2206.98  5338.7 2211.09  5351.0 2217.42  5366.8 2219.49  5396.3 2219.93
#Mann=7,-1,0
  4590.1    0.05       0  4953.6    0.12       0  4999.4    0.07       0
  5016.9    0.12       0  5066.7    0.05       0  5234.4    0.12       0
  5281.9    0.05       0
Bank Sta=4999.4,5016.9
Exp/Cntr=0.3,0.1

Type RM Length L Ch R = 1,1089043,544,544,544
BEGIN DESCRIPTION:
Clear Fork Brazos Rv 363.0
END DESCRIPTION:
XS GIS Cut Line= 3
      1291641.57      6949622.83      1291955.00      6949138.00
      1292154.98      6948788.03
#Sta/Elev= 30
  4417.3 2212.85  4654.6 2202.19  4812.3 2201.67  4944.0 2200.39  4950.8 2201.23
  4965.9 2191.77  4987.0 2190.33  4997.5 2188.18  5000.1 2182.42  5002.0 2181.42
  5017.6 2182.42  5029.9 2183.12  5040.0 2188.99  5052.2 2190.92  5090.4 2189.91
  5110.5 2189.74  5126.4 2192.52  5132.8 2197.19  5142.2 2201.56  5155.9 2203.71
  5185.4 2205.98  5191.1 2204.80  5201.2 2206.92  5206.9 2205.43  5222.8 2208.86
  5228.6 2208.56  5266.0 2214.37  5317.1 2218.43  5346.6 2224.57  5397.7 2229.23
#Mann=7,-1,0
  4417.3    0.05       0  4812.3    0.12       0  4944.0    0.05       0
  5000.1    0.05       0  5017.6    0.05       0  5090.4    0.12       0
  5206.9    0.05       0
Bank Sta=5000.1,5017.6
Exp/Cntr=0.3,0.1

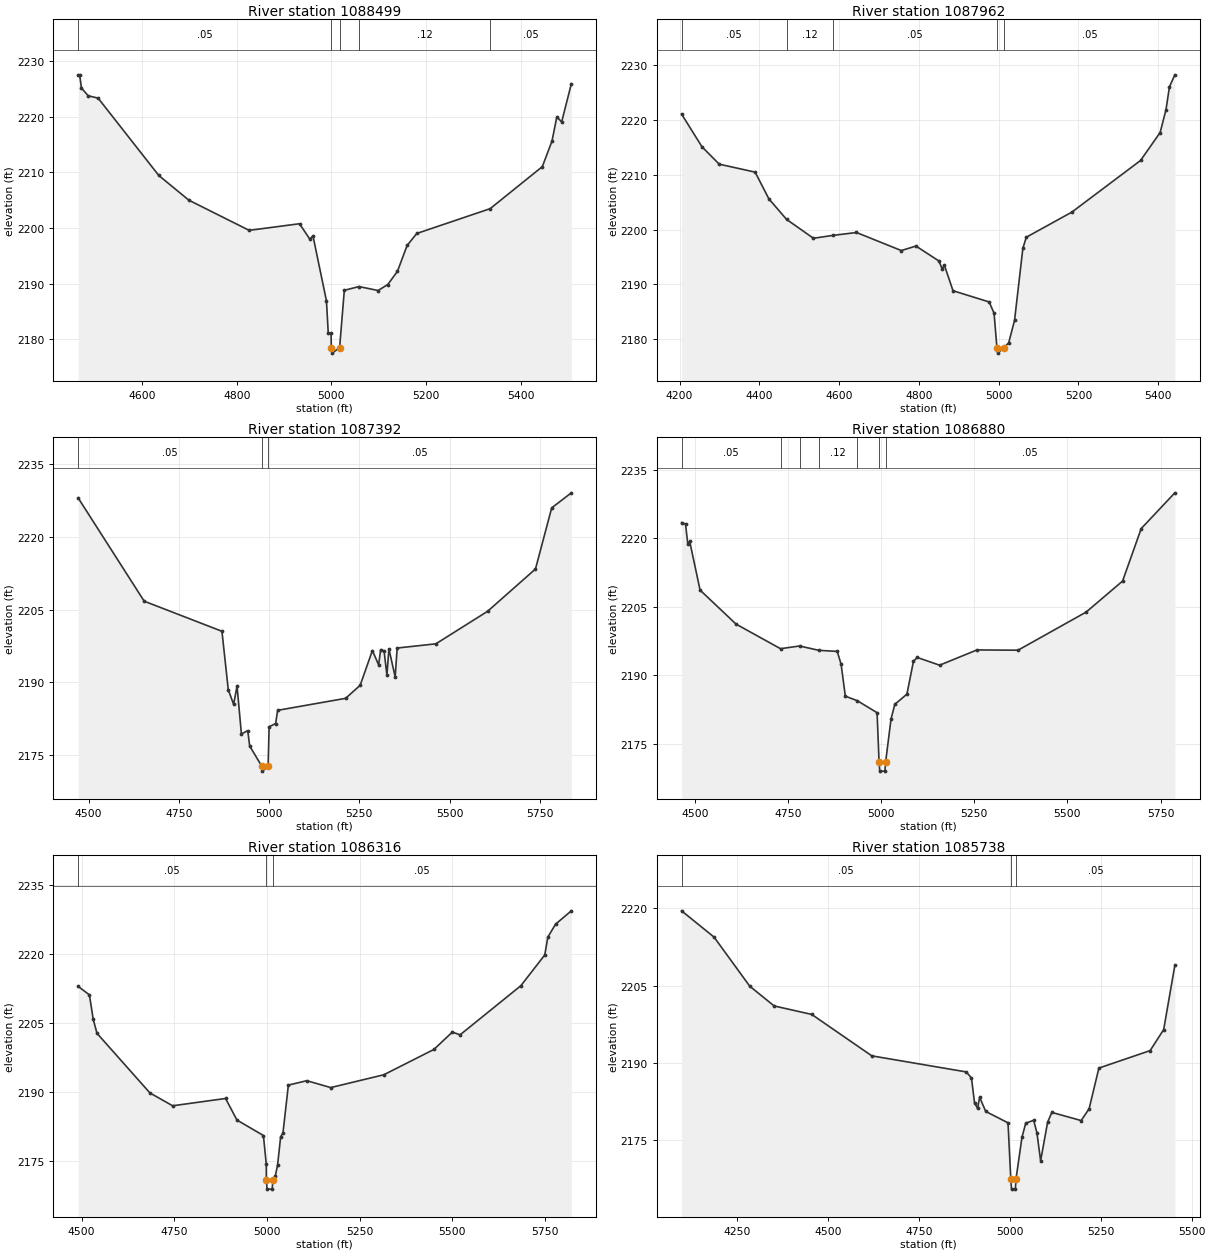
Type RM Length L Ch R = 1,1088499,537,537,537
BEGIN DESCRIPTION:
Clear Fork Brazos Rv 362.0
END DESCRIPTION:
XS GIS Cut Line= 3
      1291904.99      6949888.01      1292255.00      6949488.00
      1292354.99      6948988.03
#Sta/Elev= 30
  4465.1 2227.55  4468.4 2227.55  4472.2 2225.17  4486.5 2223.78  4507.4 2223.36
  4635.5 2209.45  4699.1 2205.00  4826.3 2199.58  4932.6 2200.77  4954.4 2198.00
  4961.0 2198.59  4989.5 2186.91  4993.3 2181.10  4999.2 2181.10  4999.8 2178.50
  5001.7 2177.50  5017.3 2178.50  5027.2 2188.80  5058.2 2189.47  5098.6 2188.76
  5119.0 2189.84  5139.4 2192.21  5159.8 2196.87  5180.2 2199.02  5335.1 2203.48
  5445.3 2211.04  5465.7 2215.64  5475.9 2219.99  5486.1 2219.08  5506.5 2225.94
#Mann=5,-1,0
  4465.1    0.05       0  4999.8    0.05       0  5017.3    0.05       0
  5058.2    0.12       0  5335.1    0.05       0
Bank Sta=4999.8,5017.3
Exp/Cntr=0.3,0.1

Type RM Length L Ch R = 1,1087962,570,570,570
BEGIN DESCRIPTION:
Clear Fork Brazos Rv 361.0
END DESCRIPTION:
XS GIS Cut Line= 3
      1292054.99      6949938.00      1292755.00      6949538.00
      1293004.97      6949188.04
#Sta/Elev= 30
  4205.2 2221.03  4256.3 2215.08  4299.5 2211.91  4389.5 2210.46  4424.0 2205.59
  4468.3 2201.85  4535.6 2198.41  4584.3 2198.93  4643.6 2199.46  4755.9 2196.17
  4792.6 2196.99  4850.2 2194.27  4858.1 2192.86  4863.9 2193.50  4885.5 2188.85
  4976.2 2186.80  4988.4 2184.74  4995.6 2178.48  4997.4 2177.48  5013.1 2178.48
  5025.0 2179.35  5039.7 2183.43  5060.6 2196.59  5069.2 2198.60  5183.5 2203.18
  5355.5 2212.58  5404.7 2217.68  5419.4 2221.87  5428.0 2226.02  5441.5 2228.19
#Mann=5,-1,0
  4205.2    0.05       0  4468.3    0.12       0  4584.3    0.05       0
  4995.6    0.05       0  5013.1    0.05       0
Bank Sta=4995.6,5013.1
Exp/Cntr=0.3,0.1

Type RM Length L Ch R = 1,1087392,512,512,512
BEGIN DESCRIPTION:
Clear Fork Brazos Rv 360.0
END DESCRIPTION:
XS GIS Cut Line= 3
      1292554.99      6950488.02      1292755.00      6949988.00
      1293105.01      6949237.98
#Sta/Elev= 30
  4471.0 2228.09  4654.1 2206.75  4869.5 2200.54  4887.0 2188.47  4901.8 2185.46
  4911.3 2189.22  4923.4 2179.34  4940.9 2180.03  4946.3 2176.86  4979.9 2172.67
  4981.8 2171.67  4997.4 2172.67  5000.1 2180.83  5018.2 2181.49  5023.7 2184.22
  5212.1 2186.70  5252.3 2189.39  5286.2 2196.56  5303.5 2193.60  5309.1 2196.75
  5318.5 2196.49  5326.4 2191.49  5331.9 2196.92  5349.3 2191.12  5354.8 2197.08
  5462.0 2197.95  5605.4 2204.67  5737.9 2213.40  5782.8 2226.01  5837.2 2229.12
#Mann=3,-1,0
  4471.0    0.05       0  4979.9    0.05       0  4997.4    0.05       0
Bank Sta=4979.9,4997.4
Exp/Cntr=0.3,0.1

Type RM Length L Ch R = 1,1086880,564,564,564
BEGIN DESCRIPTION:
Clear Fork Brazos Rv 359.0
END DESCRIPTION:
XS GIS Cut Line= 3
      1293355.01      6950538.04      1293205.00      6950038.00
      1293155.00      6949238.02
#Sta/Elev= 30
  4464.7 2223.38  4475.2 2223.06  4481.3 2218.79  4486.5 2219.26  4514.3 2208.61
  4610.9 2201.16  4730.2 2195.78  4781.3 2196.37  4833.2 2195.42  4882.4 2195.19
  4892.8 2192.36  4904.1 2185.39  4936.3 2184.39  4989.3 2181.77  4994.6 2170.98
  4996.5 2168.98  5010.3 2168.98  5012.2 2170.98  5026.8 2180.42  5036.9 2183.60
  5069.4 2185.84  5086.9 2193.03  5097.0 2193.86  5157.1 2192.17  5257.3 2195.51
  5367.5 2195.45  5550.4 2203.80  5648.0 2210.58  5698.1 2222.08  5788.3 2229.90
#Mann=7,-1,0
  4464.7    0.05       0  4730.2    0.12       0  4781.3    0.05       0
  4833.2    0.12       0  4936.3    0.05       0  4994.6    0.05       0
  5012.2    0.05       0
Bank Sta=4994.6,5012.2
Exp/Cntr=0.3,0.1

Type RM Length L Ch R = 1,1086316,578,578,578
BEGIN DESCRIPTION:
Clear Fork Brazos Rv 358.0
END DESCRIPTION:
XS GIS Cut Line= 3
      1293605.00      6950388.01      1293705.00      6949888.00
      1293204.99      6949237.98
#Sta/Elev= 30
  4490.6 2212.98  4521.2 2211.13  4531.4 2205.82  4541.6 2202.76  4684.4 2189.78
  4745.6 2186.99  4888.3 2188.58  4918.9 2183.89  4990.3 2180.52  4998.0 2174.35
  4998.3 2170.85  5000.2 2168.85  5014.0 2168.85  5015.8 2170.85  5022.3 2171.67
  5028.6 2174.11  5036.8 2180.25  5043.1 2181.10  5057.6 2191.49  5107.4 2192.45
  5171.8 2190.95  5315.0 2193.74  5450.0 2199.25  5499.8 2203.03  5520.6 2202.43
  5684.6 2213.13  5749.0 2219.82  5757.2 2223.69  5778.0 2226.51  5820.6 2229.42
#Mann=3,-1,0
  4490.6    0.05       0  4998.3    0.05       0  5015.8    0.05       0
Bank Sta=4998.3,5015.8
Exp/Cntr=0.3,0.1

Type RM Length L Ch R = 1,1085738,543,543,543
BEGIN DESCRIPTION:
Clear Fork Brazos Rv 357.0
END DESCRIPTION:
XS GIS Cut Line= 3
      1293855.00      6950588.01      1294255.00      6949788.00
      1294155.00      6949338.01
#Sta/Elev= 30
  4098.4 2219.50  4187.8 2214.39  4285.7 2204.88  4352.8 2201.05  4456.2 2199.40
  4621.1 2191.37  4881.0 2188.25  4895.0 2187.06  4903.4 2182.24  4911.8 2181.18
  4917.4 2183.35  4934.1 2180.59  4995.4 2178.38  5003.0 2167.52  5005.0 2165.52
  5015.5 2165.52  5017.4 2167.52  5033.8 2175.60  5044.1 2178.31  5065.8 2178.87
  5074.8 2176.46  5085.0 2171.01  5104.2 2178.50  5115.8 2180.40  5196.4 2178.82
  5218.2 2181.10  5245.1 2189.00  5385.9 2192.39  5423.1 2196.46  5453.8 2208.91
#Mann=3,-1,0
  4098.4    0.05       0  5003.0    0.05       0  5017.4    0.05       0
Bank Sta=5003,5017.4
Exp/Cntr=0.3,0.1

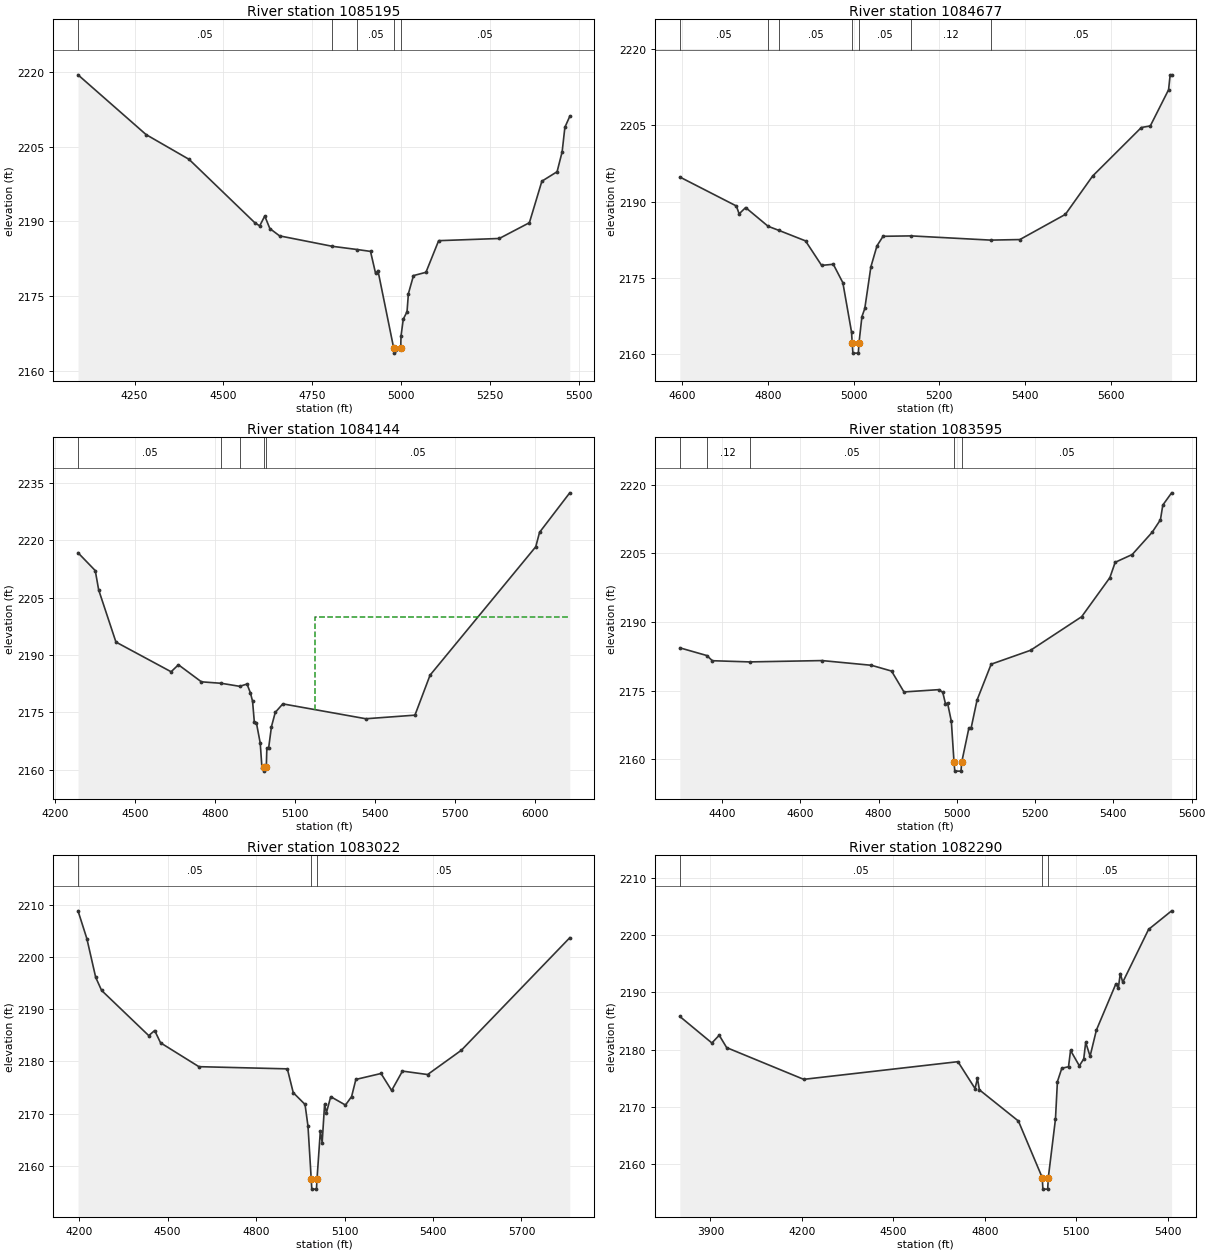
Type RM Length L Ch R = 1,1085195,518,518,518
BEGIN DESCRIPTION:
Clear Fork Brazos Rv 356.0
END DESCRIPTION:
XS GIS Cut Line= 3
      1295405.01      6950238.01      1294705.00      6949638.00
      1294405.03      6949288.04
#Sta/Elev= 30
  4091.1 2219.37  4282.6 2207.39  4403.4 2202.43  4587.8 2189.76  4602.0 2189.09
  4616.3 2191.07  4630.6 2188.56  4658.0 2187.09  4806.3 2185.00  4876.9 2184.35
  4913.7 2183.98  4928.0 2179.56  4934.6 2180.14  4978.9 2164.59  4980.9 2163.59
  4998.6 2164.59  4999.4 2166.98  5005.9 2170.41  5016.4 2171.89  5020.2 2175.50
  5034.5 2179.13  5069.6 2179.79  5105.3 2186.13  5275.9 2186.57  5360.5 2189.73
  5395.6 2198.05  5438.4 2199.95  5452.6 2203.95  5460.3 2208.85  5474.0 2211.05
#Mann=5,-1,0
  4091.1    0.05       0  4806.3    0.12       0  4876.9    0.05       0
  4978.9    0.05       0  4998.6    0.05       0
Bank Sta=4978.9,4998.6
Exp/Cntr=0.3,0.1

Type RM Length L Ch R = 1,1084677,533,533,533
BEGIN DESCRIPTION:
Clear Fork Brazos Rv 355.0
END DESCRIPTION:
XS GIS Cut Line= 3
      1295354.98      6949787.96      1295155.00      6949438.00
      1294654.98      6948887.98
#Sta/Elev= 30
  4595.1 2194.81  4726.8 2189.13  4733.3 2187.58  4748.4 2188.82  4800.9 2185.14
  4826.0 2184.34  4888.0 2182.28  4925.5 2177.47  4952.8 2177.69  4975.1 2174.06
  4995.3 2164.39  4996.9 2162.25  4998.5 2160.25  5011.1 2160.25  5012.7 2162.25
  5019.5 2167.40  5026.2 2169.01  5040.4 2177.18  5054.6 2181.31  5068.8 2183.18
  5134.2 2183.26  5319.5 2182.43  5387.7 2182.54  5493.8 2187.48  5557.3 2195.00
  5670.9 2204.53  5691.8 2204.84  5734.4 2211.94  5738.1 2214.87  5741.5 2214.87
#Mann=7,-1,0
  4595.1    0.05       0  4800.9    0.12       0  4826.0    0.05       0
  4996.9    0.05       0  5012.7    0.05       0  5134.2    0.12       0
  5319.5    0.05       0
Bank Sta=4996.9,5012.7
Exp/Cntr=0.3,0.1

Type RM Length L Ch R = 1,1084144,549,549,549
BEGIN DESCRIPTION:
Clear Fork Brazos Rv 354.0
END DESCRIPTION:
XS GIS Cut Line= 3
      1295954.97      6949687.97      1295505.00      6949138.00
      1294704.98      6948337.98
#Sta/Elev= 30
  4286.7 2216.76  4351.3 2212.09  4364.2 2207.02  4428.8 2193.40  4635.5 2185.63
  4662.8 2187.46  4748.9 2183.00  4823.7 2182.61  4892.5 2181.82  4919.8 2182.42
  4932.7 2180.06  4940.6 2177.90  4947.0 2172.61  4954.9 2172.29  4969.3 2166.97
  4975.8 2160.45  4982.0 2160.64  4984.0 2159.64  4992.0 2160.64  4994.1 2165.71
  5000.8 2165.71  5011.4 2171.29  5025.6 2175.01  5053.9 2177.23  5365.0 2173.34
  5548.8 2174.28  5605.4 2184.74  6001.4 2218.33  6015.5 2222.09  6128.7 2232.43
#Mann=5,-1,0
  4286.7    0.05       0  4823.7    0.12       0  4892.5    0.05       0
  4982.0    0.05       0  4992.0    0.05       0
#XS Ineff=2,0
       0                 5174.10    0.00 2199.85
Permanent Ineff=
       F       F
Bank Sta=4982,4992
Exp/Cntr=0.3,0.1

Type RM Length L Ch R = 1,1083595,573,573,573
BEGIN DESCRIPTION:
Clear Fork Brazos Rv 353.0
END DESCRIPTION:
XS GIS Cut Line= 3
      1295754.99      6949337.97      1295455.00      6948688.00
      1295155.00      6948237.99
#Sta/Elev= 30
  4292.1 2184.37  4361.0 2182.69  4375.1 2181.56  4470.2 2181.30  4655.5 2181.59
  4781.7 2180.56  4833.1 2179.30  4864.8 2174.74  4953.3 2175.24  4963.9 2174.67
  4970.8 2172.19  4976.3 2172.28  4985.9 2168.31  4992.7 2159.45  4994.7 2157.45
  5010.5 2157.45  5012.5 2159.45  5030.5 2166.77  5036.5 2166.88  5051.5 2172.95
  5087.6 2180.80  5188.2 2183.83  5318.9 2191.17  5391.0 2199.70  5404.6 2203.05
  5448.1 2204.75  5499.2 2209.62  5520.2 2212.33  5526.3 2215.55  5548.8 2218.22
#Mann=5,-1,0
  4292.1    0.05       0  4361.0    0.12       0  4470.2    0.05       0
  4992.7    0.05       0  5012.5    0.05       0
Bank Sta=4992.7,5012.5
Exp/Cntr=0.3,0.1

Type RM Length L Ch R = 1,1083022,732,732,732
BEGIN DESCRIPTION:
Clear Fork Brazos Rv 352.0
END DESCRIPTION:
XS GIS Cut Line= 3
      1296005.00      6949587.96      1296005.00      6948788.00
      1295479.88      6948097.07
#Sta/Elev= 30
  4196.0 2208.92  4226.0 2203.59  4256.0 2196.15  4276.0 2193.64  4436.0 2184.96
  4456.0 2185.94  4476.0 2183.58  4606.0 2179.00  4906.0 2178.58  4926.0 2174.01
  4966.0 2171.75  4976.0 2167.58  4986.9 2157.49  4988.9 2155.49  5004.7 2155.49
  5006.7 2157.49  5017.8 2166.57  5024.1 2164.44  5032.3 2171.76  5038.6 2170.19
  5053.1 2173.24  5103.1 2171.63  5123.9 2173.26  5138.4 2176.55  5223.7 2177.69
  5259.7 2174.43  5296.4 2178.15  5381.7 2177.49  5496.1 2182.15  5863.8 2203.75
#Mann=3,-1,0
  4196.0    0.05       0  4986.9    0.05       0  5006.7    0.05       0
Bank Sta=4986.9,5006.7
Exp/Cntr=0.3,0.1

Type RM Length L Ch R = 1,1082290,360,360,360
BEGIN DESCRIPTION:
Mapping XS 8f4ba3d4
END DESCRIPTION:
XS GIS Cut Line= 3
      1296635.88      6949265.78      1296363.85      6948568.70
      1295692.26      6948024.63
#Sta/Elev= 30
  3800.0 2185.78  3905.0 2181.16  3929.0 2182.51  3953.5 2180.35  4206.1 2174.82
  4711.9 2177.90  4767.9 2173.22  4775.9 2174.97  4782.3 2172.99  4910.2 2167.55
  4988.4 2157.68  4990.4 2155.68  5006.2 2155.68  5008.2 2157.68  5031.7 2167.89
  5038.1 2174.43  5052.5 2176.75  5074.5 2177.02  5081.2 2179.86  5110.0 2177.18
  5124.4 2178.38  5130.8 2181.26  5145.2 2178.85  5166.0 2183.42  5229.9 2191.48
  5237.9 2190.76  5244.3 2193.27  5252.3 2191.75  5337.0 2200.96  5412.6 2204.20
#Mann=3,-1,0
  3800.0    0.05       0  4988.4    0.05       0  5008.2    0.05       0
Bank Sta=4988.4,5008.2
Exp/Cntr=0.3,0.1

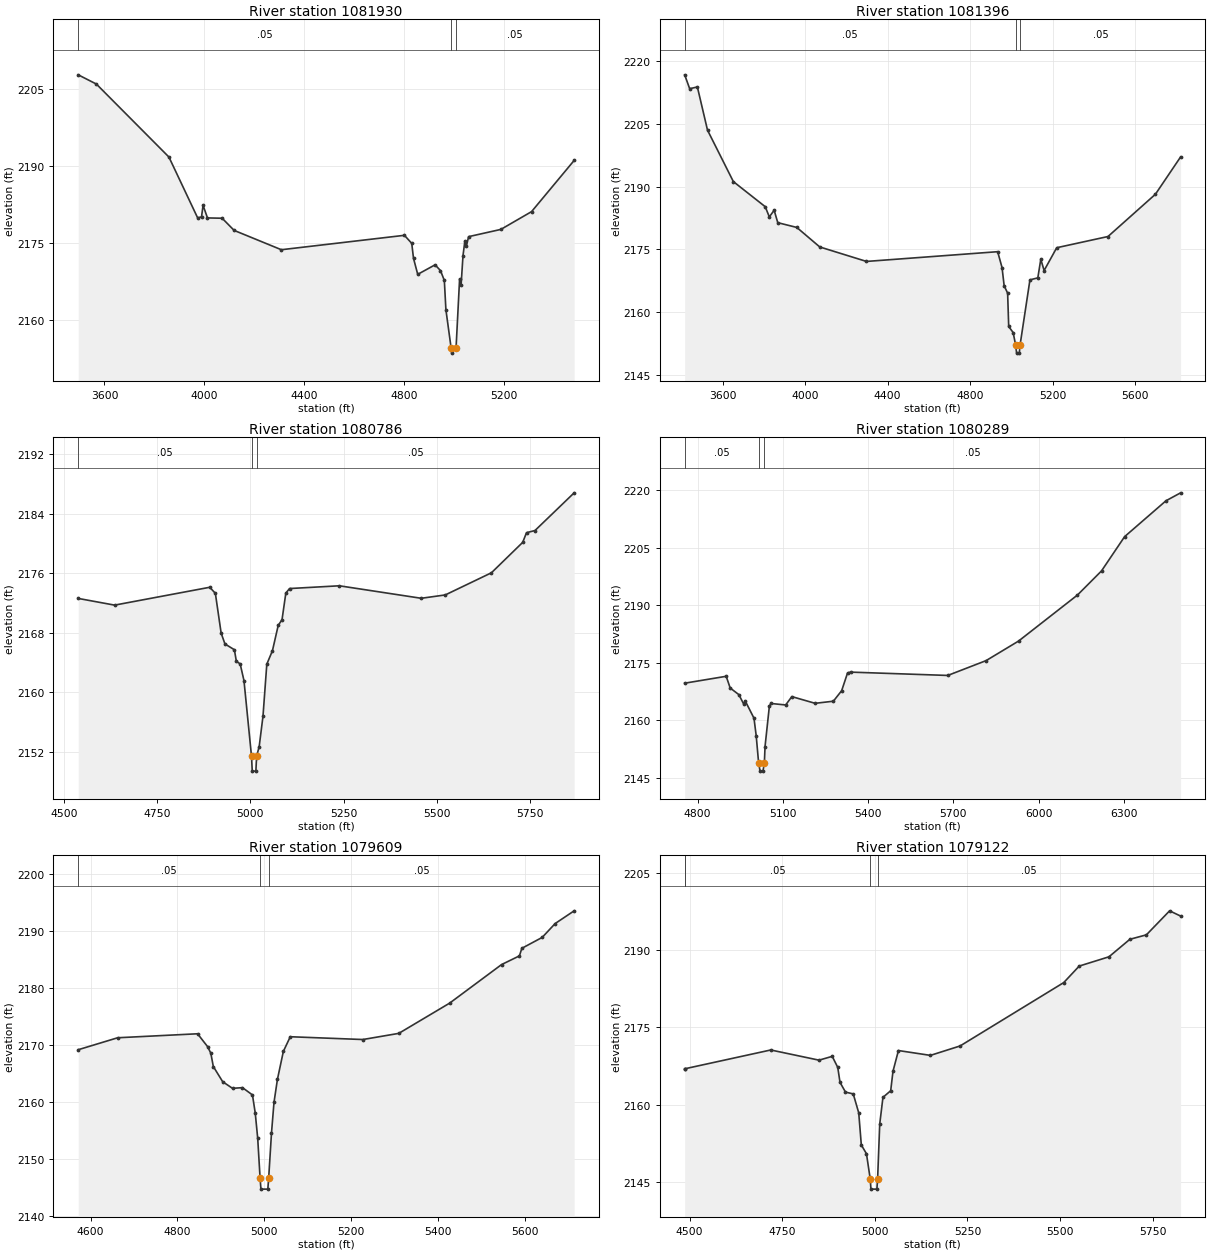
Type RM Length L Ch R = 1,1081930,534,534,534
BEGIN DESCRIPTION:
Clear Fork Brazos Rv 351.0
END DESCRIPTION:
XS GIS Cut Line= 3
      1296927.58      6949630.68      1296355.00      6948238.00
      1296087.55      6947837.60
#Sta/Elev= 30
  3494.8 2207.80  3567.6 2206.00  3858.3 2191.77  3973.4 2179.91  3988.9 2180.11
  3995.1 2182.35  4012.8 2179.90  4071.6 2179.84  4119.5 2177.47  4308.8 2173.70
  4802.0 2176.51  4831.3 2174.94  4838.4 2172.01  4855.3 2168.90  4924.9 2170.76
  4946.5 2169.63  4961.9 2167.71  4968.2 2162.00  4989.1 2154.54  4991.1 2153.54
  5008.9 2154.54  5023.1 2168.03  5029.1 2166.86  5036.7 2172.55  5044.1 2175.36
  5050.2 2174.39  5059.2 2176.25  5188.3 2177.66  5311.5 2181.13  5482.1 2191.11
#Mann=3,-1,0
  3494.8    0.05       0  4989.1    0.05       0  5008.9    0.05       0
Bank Sta=4989.1,5008.9
Exp/Cntr=0.3,0.1

Type RM Length L Ch R = 1,1081396,610,610,610
BEGIN DESCRIPTION:
Clear Fork Brazos Rv 350.0
END DESCRIPTION:
XS GIS Cut Line= 3
      1297105.00      6949637.99      1296755.00      6948088.00
      1296604.99      6947287.95
#Sta/Elev= 30
  3416.7 2216.72  3440.9 2213.40  3478.2 2213.82  3527.3 2203.49  3652.5 2191.19
  3807.0 2185.18  3826.8 2182.74  3850.2 2184.33  3867.8 2181.36  3960.0 2180.22
  4071.3 2175.55  4297.6 2172.09  4933.2 2174.42  4954.5 2170.61  4964.7 2166.26
  4981.5 2164.51  4986.7 2156.53  5008.3 2155.08  5020.0 2152.16  5025.0 2150.16
  5038.0 2150.16  5042.0 2152.16  5089.6 2167.68  5127.8 2168.16  5142.2 2172.60
  5158.3 2169.92  5219.4 2175.37  5467.8 2178.05  5697.6 2188.16  5819.7 2197.09
#Mann=3,-1,0
  3416.7    0.05       0  5020.0    0.05       0  5042.0    0.05       0
Bank Sta=5020,5042
Exp/Cntr=0.3,0.1

Type RM Length L Ch R = 1,1080786,497,497,497
BEGIN DESCRIPTION:
Clear Fork Brazos Rv 349.0
END DESCRIPTION:
XS GIS Cut Line= 3
      1297077.94      6948653.68      1297209.70      6947994.89
      1297018.44      6947365.86
#Sta/Elev= 30
  4538.5 2172.59  4636.1 2171.69  4891.0 2174.09  4906.1 2173.28  4921.6 2167.93
  4931.8 2166.47  4957.1 2165.69  4962.4 2164.13  4972.6 2163.79  4982.8 2161.54
  5003.0 2151.37  5005.0 2149.37  5014.7 2149.37  5016.7 2151.37  5023.6 2152.68
  5033.8 2156.77  5044.0 2163.75  5059.1 2165.56  5074.6 2168.97  5084.8 2169.73
  5095.0 2173.31  5105.0 2173.92  5238.4 2174.29  5457.9 2172.61  5522.3 2173.06
  5646.1 2176.04  5729.9 2180.13  5740.1 2181.43  5762.8 2181.72  5867.8 2186.79
#Mann=3,-1,0
  4538.5    0.05       0  5003.0    0.05       0  5016.7    0.05       0
Bank Sta=5003,5016.7
Exp/Cntr=0.3,0.1

Type RM Length L Ch R = 1,1080289,680,680,680
BEGIN DESCRIPTION:
Clear Fork Brazos Rv 348.0
END DESCRIPTION:
XS GIS Cut Line= 3
      1297516.58      6948576.20      1297555.00      6948338.00
      1297155.01      6946888.04
#Sta/Elev= 30
  4754.6 2169.68  4900.7 2171.48  4914.8 2168.42  4945.2 2166.70  4962.5 2164.21
  4967.5 2165.08  4998.5 2160.55  5006.3 2155.99  5015.0 2148.74  5020.0 2146.74
  5030.0 2146.74  5035.0 2148.74  5037.4 2153.14  5052.6 2163.65  5058.1 2164.39
  5110.0 2164.00  5131.7 2166.18  5213.7 2164.43  5277.9 2164.98  5307.1 2167.73
  5327.8 2172.35  5338.2 2172.57  5680.5 2171.70  5815.4 2175.57  5929.5 2180.66
  6137.0 2192.68  6221.6 2198.97  6302.9 2207.91  6448.5 2217.27  6500.0 2219.34
#Mann=3,-1,0
  4754.6    0.05       0  5015.0    0.05       0  5035.0    0.05       0
Bank Sta=5015,5035
Exp/Cntr=0.3,0.1

Type RM Length L Ch R = 1,1079609,487,487,487
BEGIN DESCRIPTION:
Mapping XS 767a338e
END DESCRIPTION:
XS GIS Cut Line= 3
      1298064.02      6947994.88      1297443.47      6947642.10
      1297341.46      6947225.53
#Sta/Elev= 30
  4571.6 2169.14  4662.5 2171.24  4846.6 2171.94  4869.6 2169.69  4877.1 2168.54
  4882.9 2166.19  4904.5 2163.52  4927.1 2162.36  4950.1 2162.48  4973.1 2161.20
  4979.5 2158.02  4985.2 2153.56  4990.6 2146.66  4992.6 2144.66  5008.5 2144.66
  5010.5 2146.66  5016.9 2154.47  5022.7 2159.88  5030.6 2163.93  5044.3 2168.85
  5060.2 2171.42  5227.4 2170.93  5310.2 2172.01  5427.4 2177.32  5547.0 2184.09
  5588.2 2185.62  5593.8 2186.95  5640.6 2188.86  5670.6 2191.30  5714.3 2193.53
#Mann=3,-1,0
  4571.6    0.05       0  4990.6    0.05       0  5010.5    0.05       0
Bank Sta=4990.6,5010.5
Exp/Cntr=0.3,0.1

Type RM Length L Ch R = 1,1079122,519,519,519
BEGIN DESCRIPTION:
Mapping XS ff68d3ba
END DESCRIPTION:
XS GIS Cut Line= 2
      1298359.42      6948058.24      1297590.27      6946962.56
#Sta/Elev= 30
  4486.9 2166.97  4488.2 2166.97  4719.3 2170.61  4849.5 2168.63  4885.2 2169.37
  4900.1 2167.22  4906.2 2164.31  4921.0 2162.42  4941.9 2162.07  4956.7 2158.40
  4963.7 2152.14  4977.6 2150.44  4987.7 2145.56  4989.7 2143.56  5005.7 2143.56
  5007.7 2145.56  5013.4 2156.21  5022.1 2161.40  5043.0 2162.69  5049.2 2166.47
  5063.9 2170.50  5150.2 2169.56  5230.3 2171.39  5510.1 2183.71  5551.9 2186.92
  5632.1 2188.72  5688.7 2192.13  5733.2 2192.99  5795.9 2197.66  5825.6 2196.64
#Mann=4,-1,0
  4486.9    0.12       0  4488.2    0.05       0  4987.7    0.05       0
  5007.7    0.05       0
Bank Sta=4987.7,5007.7
Exp/Cntr=0.3,0.1

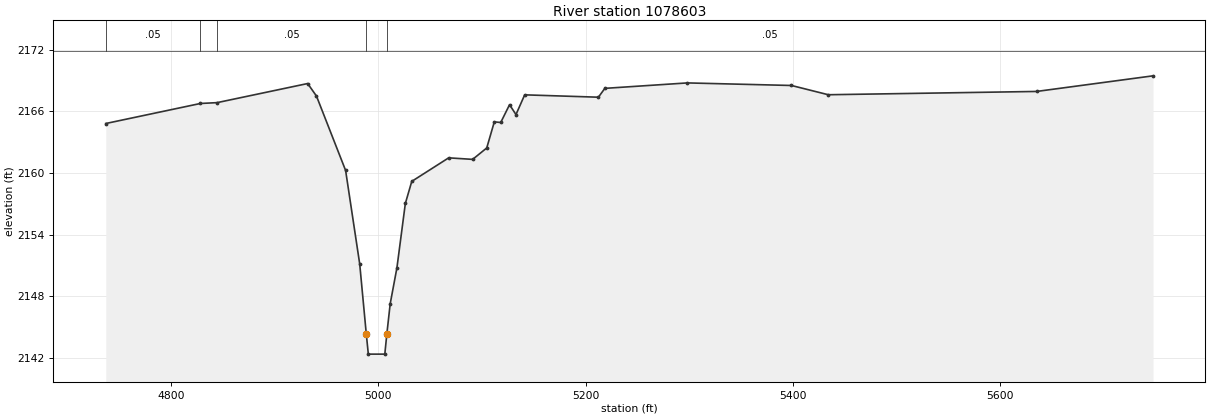
Type RM Length L Ch R = 1,1078603,644,644,644
BEGIN DESCRIPTION:
Mapping XS d02ee826
END DESCRIPTION:
XS GIS Cut Line= 2
      1298731.39      6947824.89      1298136.32      6947008.81
#Sta/Elev= 30
  4737.3 2164.83  4828.6 2166.78  4844.6 2166.86  4932.0 2168.72  4940.5 2167.50
  4968.6 2160.26  4982.2 2151.16  4988.5 2144.39  4990.5 2142.39  5006.4 2142.39
  5008.4 2144.39  5011.6 2147.29  5018.1 2150.80  5026.2 2157.05  5032.4 2159.20
  5068.0 2161.49  5091.1 2161.34  5104.7 2162.45  5112.0 2164.99  5118.2 2164.93
  5126.7 2166.66  5132.9 2165.70  5141.3 2167.62  5212.4 2167.39  5218.6 2168.25
  5298.2 2168.78  5398.6 2168.53  5434.1 2167.63  5635.0 2167.95  5747.3 2169.47
#Mann=5,-1,0
  4737.3    0.05       0  4828.6    0.12       0  4844.6    0.05       0
  4988.5    0.05       0  5008.4    0.05       0
Bank Sta=4988.5,5008.4
Exp/Cntr=0.3,0.1