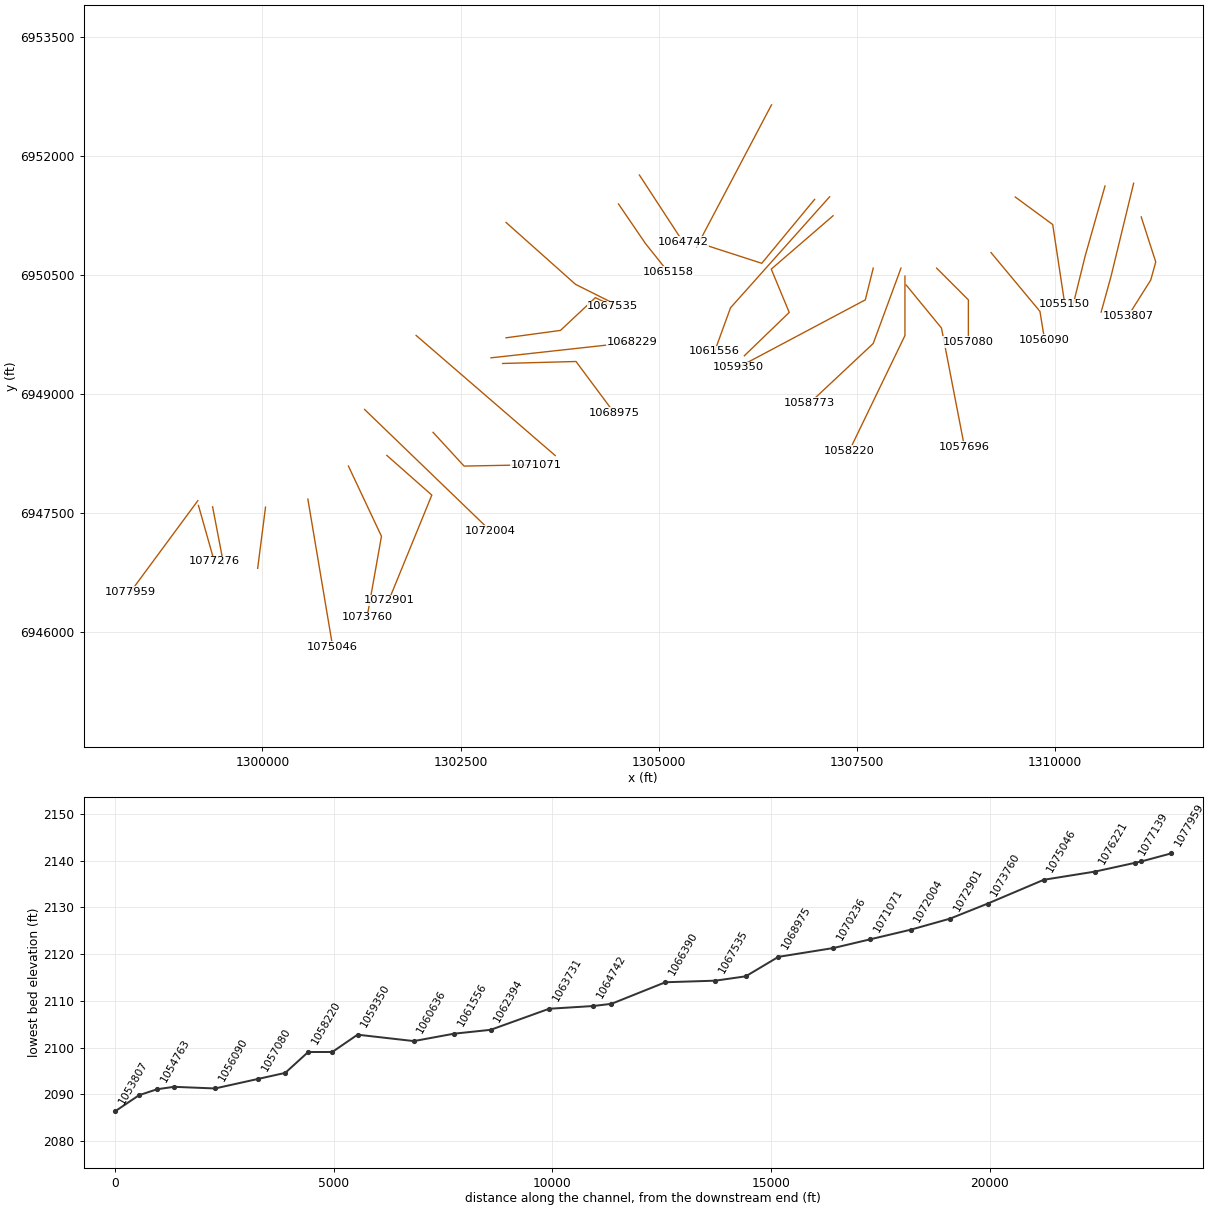
HEC-RAS study Clear Fork Brazos Rv.prj: Clear Fork Brazos Rv Base Level Engineering

--- Clear Fork Brazos Rv.g01 (geometry) --- (continued)

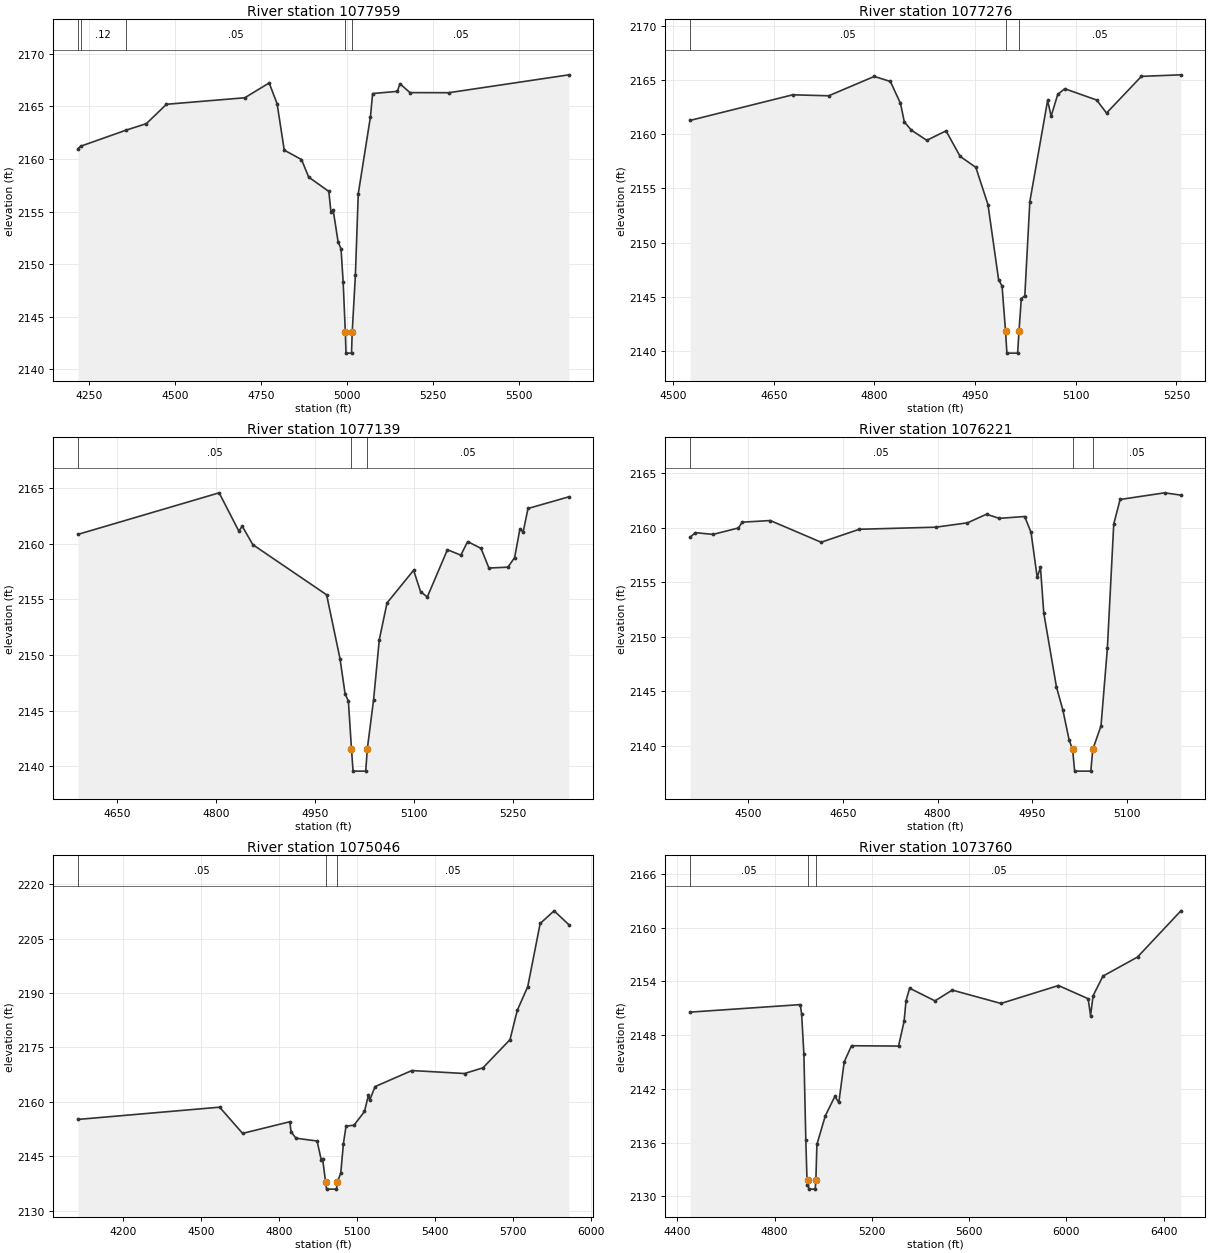
Type RM Length L Ch R = 1,1077959,683,683,683
BEGIN DESCRIPTION:
Mapping XS 7665d5bb
END DESCRIPTION:
XS GIS Cut Line= 2
      1299186.60      6947654.93      1298339.11      6946506.97
#Sta/Elev= 30
  4217.4 2160.98  4224.9 2161.21  4357.1 2162.74  4416.2 2163.36  4474.6 2165.20
  4702.3 2165.82  4773.2 2167.23  4796.3 2165.25  4817.1 2160.84  4867.2 2159.95
  4888.1 2158.28  4946.6 2156.92  4952.8 2154.98  4959.4 2155.12  4973.7 2152.11
  4982.1 2151.47  4988.3 2148.32  4994.6 2143.55  4996.6 2141.55  5012.6 2141.55
  5014.6 2143.55  5023.8 2148.93  5032.2 2156.69  5067.7 2164.03  5073.9 2166.22
  5145.8 2166.43  5153.3 2167.15  5182.6 2166.31  5295.2 2166.30  5644.3 2168.00
#Mann=5,-1,0
  4217.4    0.05       0  4224.9    0.12       0  4357.1    0.05       0
  4994.6    0.05       0  5014.6    0.05       0
Bank Sta=4994.6,5014.6
Exp/Cntr=0.3,0.1

Type RM Length L Ch R = 1,1077276,137,137,137
BEGIN DESCRIPTION:
Mapping XS 839c7847
END DESCRIPTION:
XS GIS Cut Line= 2
      1299194.67      6947595.35      1299393.97      6946891.42
#Sta/Elev= 30
  4525.1 2161.26  4678.2 2163.62  4731.8 2163.53  4799.7 2165.31  4823.7 2164.85
  4838.8 2162.83  4844.5 2161.13  4854.9 2160.37  4878.0 2159.43  4906.7 2160.30
  4927.7 2157.95  4951.1 2156.94  4969.2 2153.51  4985.0 2146.61  4990.2 2146.00
  4995.4 2141.83  4997.4 2139.83  5013.4 2139.83  5015.4 2141.83  5018.9 2144.86
  5024.1 2145.11  5031.6 2153.79  5058.1 2163.10  5063.3 2161.65  5073.2 2163.66
  5083.6 2164.18  5131.2 2163.14  5145.9 2161.94  5197.9 2165.32  5256.7 2165.46
#Mann=3,-1,0
  4525.1    0.05       0  4995.4    0.05       0  5015.4    0.05       0
Bank Sta=4995.4,5015.4
Exp/Cntr=0.3,0.1

Type RM Length L Ch R = 1,1077139,918,918,918
BEGIN DESCRIPTION:
Mapping XS 75dd4362
END DESCRIPTION:
XS GIS Cut Line= 2
      1299373.20      6947578.30      1299513.46      6946847.24
#Sta/Elev= 30
  4590.2 2160.86  4804.3 2164.60  4834.2 2161.15  4839.3 2161.60  4855.3 2159.94
  4967.3 2155.42  4987.6 2149.67  4995.3 2146.51  5000.3 2145.85  5005.0 2141.55
  5007.4 2139.55  5026.6 2139.55  5029.0 2141.55  5038.5 2145.97  5047.2 2151.39
  5058.9 2154.69  5099.2 2157.63  5109.8 2155.70  5120.0 2155.23  5150.5 2159.48
  5170.9 2158.99  5181.1 2160.21  5201.5 2159.60  5213.4 2157.83  5242.2 2157.91
  5252.4 2158.77  5260.3 2161.31  5265.4 2161.10  5272.7 2163.19  5334.6 2164.24
#Mann=3,-1,0
  4590.2    0.05       0  5005.0    0.03       0  5029.0    0.05       0
Bank Sta=5005,5029
Exp/Cntr=0.3,0.1

Type RM Length L Ch R = 1,1076221,1175,1175,1175
BEGIN DESCRIPTION:
Mapping XS 7752ce69
END DESCRIPTION:
XS GIS Cut Line= 2
      1300040.67      6947574.21      1299941.63      6946802.44
#Sta/Elev= 30
  4407.6 2159.09  4415.9 2159.53  4444.1 2159.37  4484.4 2159.96  4490.4 2160.49
  4534.8 2160.64  4615.5 2158.65  4676.0 2159.84  4797.0 2160.03  4847.4 2160.43
  4877.6 2161.22  4897.8 2160.84  4938.1 2161.01  4948.2 2159.55  4958.0 2155.43
  4963.1 2156.36  4968.4 2152.16  4988.5 2145.38  4998.6 2143.28  5008.7 2140.49
  5014.1 2139.67  5017.3 2137.67  5042.9 2137.67  5046.1 2139.67  5059.1 2141.82
  5069.2 2148.93  5079.3 2160.32  5089.4 2162.57  5159.9 2163.18  5185.7 2162.97
#Mann=3,-1,0
  4407.6    0.05       0  5014.1    0.05       0  5046.1    0.05       0
Bank Sta=5014.1,5046.1
Exp/Cntr=0.3,0.1

Type RM Length L Ch R = 1,1075046,1286,1286,1286
BEGIN DESCRIPTION:
Mapping XS e2d2d8aa
END DESCRIPTION:
XS GIS Cut Line= 2
      1300574.49      6947675.91      1300887.95      6945812.09
#Sta/Elev= 30
  4025.5 2155.13  4571.0 2158.51  4659.4 2151.28  4841.1 2154.49  4846.2 2151.69
  4865.0 2149.95  4946.2 2149.18  4962.3 2143.94  4967.3 2144.35  4978.9 2137.91
  4982.9 2135.91  5020.8 2135.91  5024.8 2137.91  5037.4 2140.34  5047.6 2148.47
  5057.7 2153.28  5088.5 2153.54  5128.7 2157.32  5144.0 2161.83  5149.0 2160.44
  5169.3 2164.18  5311.2 2168.61  5514.0 2167.79  5585.0 2169.37  5689.1 2177.14
  5716.8 2185.17  5757.4 2191.76  5805.1 2209.16  5858.8 2212.65  5915.5 2208.83
#Mann=3,-1,0
  4025.5    0.05       0  4978.9    0.05       0  5024.8    0.05       0
Bank Sta=4978.9,5024.8
Exp/Cntr=0.3,0.1

Type RM Length L Ch R = 1,1073760,859,859,859
BEGIN DESCRIPTION:
Mapping XS 37546d94
END DESCRIPTION:
XS GIS Cut Line= 3
      1301086.23      6948091.74      1301502.89      6947206.34
      1301320.68      6946182.47
#Sta/Elev= 30
  4452.2 2150.57  4905.6 2151.41  4911.1 2150.38  4920.5 2145.90  4928.4 2136.33
  4933.9 2131.31  4937.7 2131.81  4940.5 2130.81  4967.0 2130.81  4969.8 2131.81
  4974.0 2135.80  5008.9 2139.02  5047.9 2141.16  5064.2 2140.49  5086.3 2145.02
  5116.3 2146.82  5309.7 2146.78  5332.5 2149.54  5340.5 2151.84  5355.3 2153.24
  5459.5 2151.83  5530.6 2153.03  5730.7 2151.54  5967.4 2153.54  6089.3 2152.07
  6099.4 2150.19  6109.6 2152.39  6150.2 2154.59  6292.4 2156.72  6470.7 2161.88
#Mann=3,-1,0
  4452.2    0.05       0  4937.7    0.05       0  4969.8    0.05       0
Bank Sta=4937.7,4969.8
Exp/Cntr=0.3,0.1

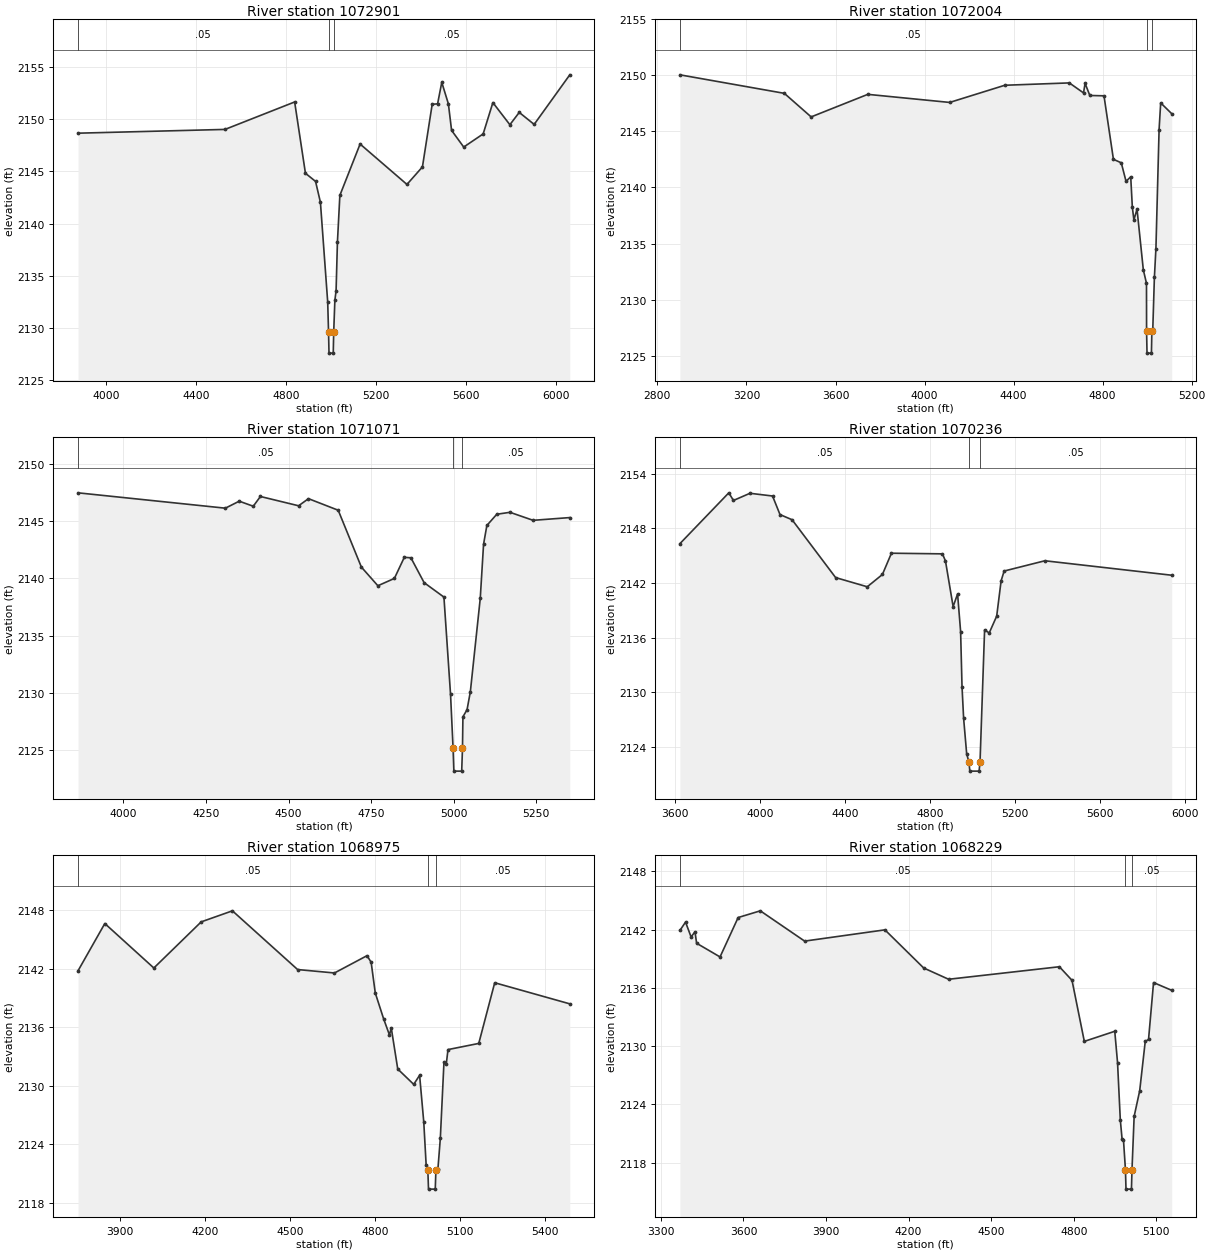
Type RM Length L Ch R = 1,1072901,897,897,897
BEGIN DESCRIPTION:
Mapping XS b0865815
END DESCRIPTION:
XS GIS Cut Line= 3
      1301570.75      6948226.35      1302137.92      6947725.90
      1301596.42      6946401.31
#Sta/Elev= 30
  3874.2 2148.67  4527.9 2149.03  4837.8 2151.66  4885.8 2144.83  4930.8 2144.05
  4952.4 2142.05  4984.8 2132.50  4988.6 2129.60  4990.6 2127.60  5009.5 2127.60
  5011.5 2129.60  5016.7 2132.65  5022.1 2133.58  5028.1 2138.24  5038.9 2142.71
  5128.9 2147.63  5337.3 2143.76  5406.2 2145.44  5449.6 2151.44  5473.6 2151.48
  5492.2 2153.54  5521.6 2151.48  5535.8 2148.94  5589.8 2147.34  5676.3 2148.60
  5719.5 2151.60  5795.1 2149.48  5836.8 2150.66  5903.1 2149.51  6061.6 2154.26
#Mann=3,-1,0
  3874.2    0.05       0  4988.6    0.05       0  5011.5    0.05       0
Bank Sta=4988.6,5011.5
Exp/Cntr=0.3,0.1

Type RM Length L Ch R = 1,1072004,933,933,933
BEGIN DESCRIPTION:
Mapping XS f71df4c9
END DESCRIPTION:
XS GIS Cut Line= 2
      1301289.59      6948806.03      1302879.60      6947272.55
#Sta/Elev= 30
  2901.0 2150.04  3370.1 2148.39  3490.5 2146.29  3745.0 2148.30  4112.8 2147.58
  4360.3 2149.11  4650.2 2149.32  4714.0 2148.43  4721.0 2149.28  4742.3 2148.20
  4805.9 2148.17  4848.3 2142.51  4883.6 2142.20  4904.9 2140.55  4926.0 2140.95
  4933.2 2138.26  4940.2 2137.11  4954.3 2138.07  4982.6 2132.66  4996.8 2131.46
  4997.2 2127.24  4999.2 2125.24  5019.0 2125.24  5021.0 2127.24  5025.1 2127.36
  5032.3 2131.98  5039.2 2134.56  5053.4 2145.15  5060.6 2147.54  5110.0 2146.58
#Mann=3,-1,0
  2901.0    0.05       0  4997.2    0.05       0  5021.0    0.05       0
Bank Sta=4997.2,5021
Exp/Cntr=0.3,0.1

Type RM Length L Ch R = 1,1071071,835,835,835
BEGIN DESCRIPTION:
Mapping XS d5739eb3
END DESCRIPTION:
XS GIS Cut Line= 3
      1302153.96      6948517.07      1302544.56      6948091.75
      1303456.04      6948109.11
#Sta/Elev= 30
  3862.3 2147.46  4308.5 2146.12  4350.5 2146.73  4393.0 2146.29  4414.6 2147.14
  4530.2 2146.33  4560.2 2146.95  4650.2 2145.94  4720.3 2140.98  4770.3 2139.35
  4820.3 2139.99  4850.3 2141.83  4870.3 2141.79  4910.3 2139.62  4970.3 2138.36
  4990.3 2129.88  4998.0 2125.17  5000.4 2123.17  5024.1 2123.17  5026.5 2125.17
  5027.8 2127.91  5040.3 2128.53  5050.3 2130.10  5080.3 2138.25  5090.3 2142.97
  5100.3 2144.61  5130.3 2145.59  5170.3 2145.76  5240.3 2145.06  5351.4 2145.30
#Mann=3,-1,0
  3862.3    0.05       0  4998.0    0.03       0  5026.5    0.05       0
Bank Sta=4998,5026.5
Exp/Cntr=0.3,0.1

Type RM Length L Ch R = 1,1070236,1261,1261,1261
BEGIN DESCRIPTION:
Mapping XS 48e021f8
END DESCRIPTION:
XS GIS Cut Line= 2
      1301940.59      6949739.23      1303694.46      6948224.24
#Sta/Elev= 30
  3621.8 2146.33  3852.3 2151.92  3874.1 2151.08  3952.0 2151.87  4058.4 2151.57
  4093.5 2149.53  4150.5 2148.96  4355.7 2142.60  4504.8 2141.59  4576.1 2142.94
  4618.7 2145.28  4859.2 2145.21  4873.4 2144.42  4909.4 2139.41  4930.4 2140.80
  4944.7 2136.66  4951.3 2130.61  4958.9 2127.11  4973.2 2123.23  4983.8 2122.32
  4988.2 2121.32  5031.8 2121.32  5036.2 2122.32  5057.7 2136.84  5079.6 2136.52
  5114.7 2138.36  5135.6 2142.25  5149.8 2143.32  5341.8 2144.45  5939.4 2142.86
#Mann=3,-1,0
  3621.8    0.05       0  4983.8    0.05       0  5036.2    0.05       0
Bank Sta=4983.8,5036.2
Exp/Cntr=0.3,0.1

Type RM Length L Ch R = 1,1068975,746,746,746
BEGIN DESCRIPTION:
Mapping XS 289b88c4
END DESCRIPTION:
XS GIS Cut Line= 3
      1303030.43      6949385.82      1303956.33      6949410.85
      1304439.04      6948761.68
#Sta/Elev= 30
  3751.4 2141.77  3846.0 2146.61  4019.0 2142.06  4186.1 2146.78  4296.2 2147.91
  4526.3 2141.90  4656.3 2141.55  4771.1 2143.32  4785.7 2142.65  4800.3 2139.50
  4829.6 2136.87  4850.4 2135.20  4856.6 2135.94  4879.6 2131.72  4935.9 2130.15
  4956.7 2131.08  4971.4 2126.29  4979.7 2121.94  4985.7 2121.43  4988.1 2119.43
  5011.9 2119.43  5014.3 2121.43  5021.4 2121.54  5029.8 2124.62  5042.6 2132.39
  5050.6 2132.19  5056.9 2133.71  5165.4 2134.34  5221.7 2140.55  5486.6 2138.39
#Mann=3,-1,0
  3751.4    0.05       0  4985.7    0.05       0  5014.3    0.05       0
Bank Sta=4985.7,5014.3
Exp/Cntr=0.3,0.1

Type RM Length L Ch R = 1,1068229,694,694,694
BEGIN DESCRIPTION:
Mapping XS 91102b93
END DESCRIPTION:
XS GIS Cut Line= 2
      1302884.66      6949457.10      1304660.54      6949652.53
#Sta/Elev= 30
  3369.1 2141.92  3389.6 2142.78  3409.7 2141.25  3423.9 2141.78  3429.8 2140.60
  3514.9 2139.19  3580.7 2143.25  3661.2 2143.94  3822.2 2140.82  4113.9 2141.98
  4254.8 2138.05  4345.3 2136.89  4747.7 2138.18  4793.6 2136.78  4838.3 2130.49
  4948.9 2131.53  4959.0 2128.30  4969.0 2122.42  4975.6 2120.39  4980.6 2120.33
  4987.7 2117.27  4989.7 2115.27  5009.5 2115.27  5011.5 2117.27  5019.3 2122.76
  5039.5 2125.41  5059.6 2130.48  5071.6 2130.69  5089.8 2136.55  5155.7 2135.75
#Mann=3,-1,0
  3369.1    0.05       0  4987.7    0.05       0  5011.5    0.05       0
Bank Sta=4987.7,5011.5
Exp/Cntr=0.3,0.1

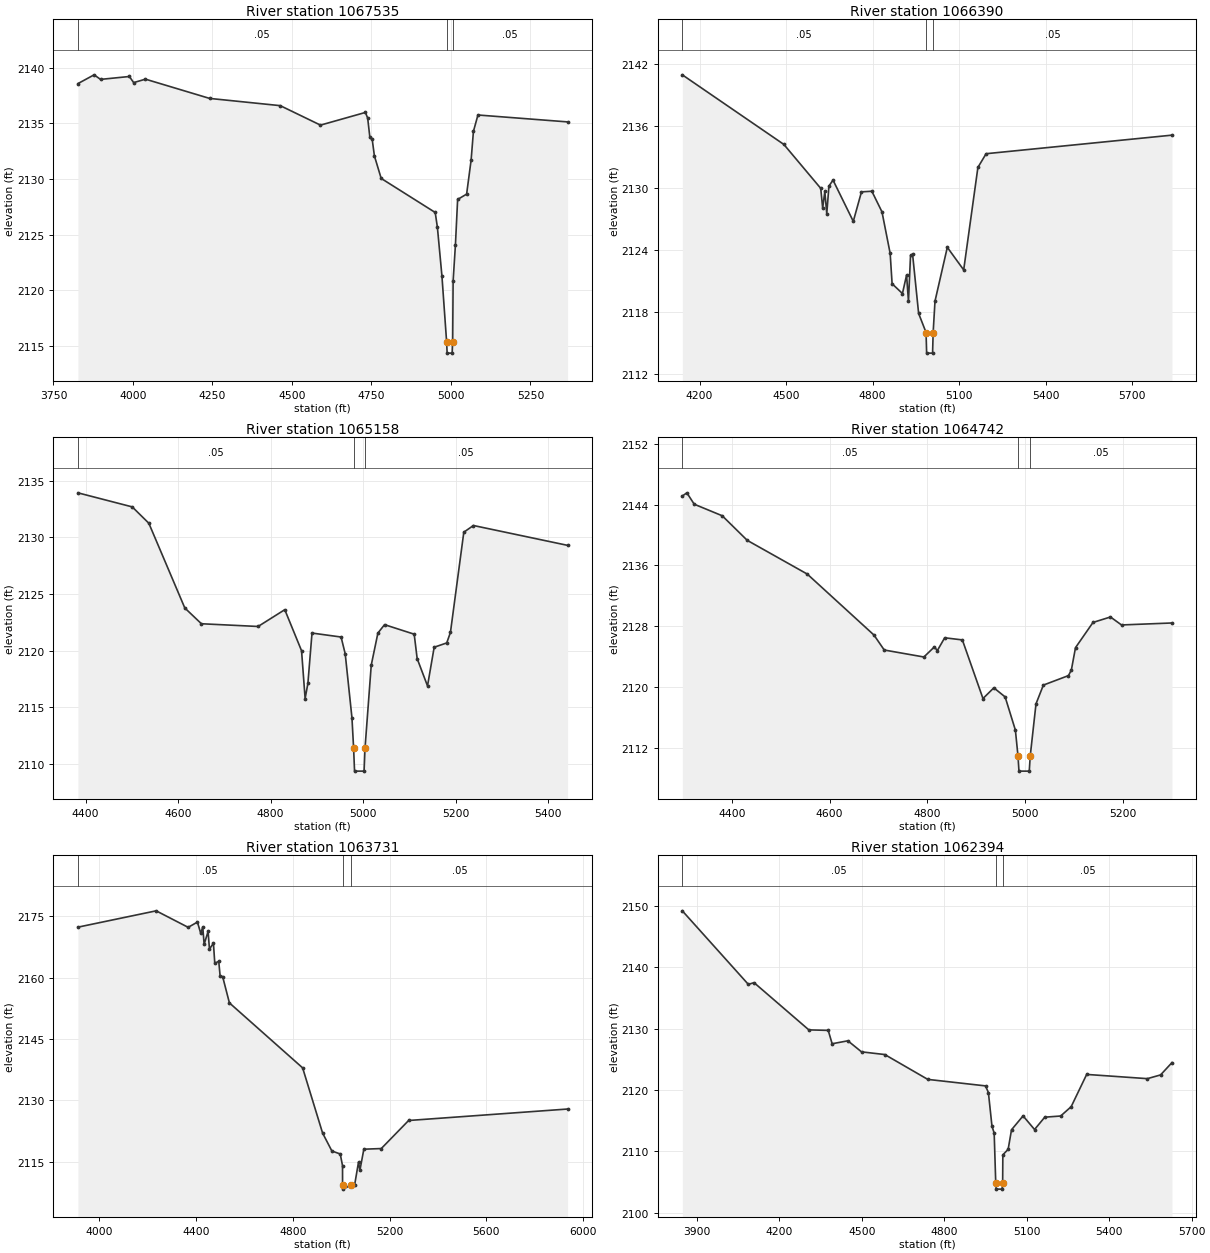
Type RM Length L Ch R = 1,1067535,1145,1145,1145
BEGIN DESCRIPTION:
Mapping XS b8860d5e
END DESCRIPTION:
XS GIS Cut Line= 4
      1303074.44      6949709.65      1303760.68      6949802.93
      1304200.40      6950216.00      1304420.17      6950109.45
#Sta/Elev= 30
  3826.8 2138.56  3877.8 2139.35  3898.0 2138.94  3988.8 2139.20  4002.1 2138.65
  4039.3 2138.96  4241.1 2137.23  4463.2 2136.58  4589.8 2134.83  4731.1 2135.97
  4738.2 2135.46  4745.1 2133.73  4752.4 2133.56  4759.3 2132.07  4780.7 2130.04
  4950.6 2126.98  4957.5 2125.64  4971.7 2121.29  4986.5 2115.34  4988.1 2114.34
  5003.9 2114.34  5005.5 2115.34  5006.9 2120.80  5014.2 2124.08  5021.1 2128.15
  5049.4 2128.63  5063.5 2131.68  5070.8 2134.27  5085.0 2135.74  5366.9 2135.12
#Mann=3,-1,0
  3826.8    0.05       0  4986.5    0.05       0  5005.5    0.05       0
Bank Sta=4986.5,5005.5
Exp/Cntr=0.3,0.1

Type RM Length L Ch R = 1,1066390,1232,1232,1232
BEGIN DESCRIPTION:
Mapping XS 958c2027
END DESCRIPTION:
XS GIS Cut Line= 3
      1303074.09      6951164.66      1303950.81      6950383.42
      1304419.58      6950149.03
#Sta/Elev= 30
  4140.1 2140.99  4492.3 2134.24  4620.2 2129.98  4626.9 2128.07  4634.4 2129.68
  4641.1 2127.52  4648.6 2130.20  4662.8 2130.78  4733.1 2126.78  4761.5 2129.64
  4797.5 2129.70  4832.6 2127.70  4861.0 2123.67  4867.7 2120.73  4903.6 2119.78
  4917.9 2121.57  4924.5 2119.01  4931.6 2123.47  4938.8 2123.58  4959.7 2117.85
  4985.5 2116.00  4987.5 2114.00  5008.1 2114.00  5010.1 2116.00  5016.5 2119.04
  5059.2 2124.26  5116.0 2122.07  5165.3 2132.01  5193.8 2133.34  5838.5 2135.14
#Mann=3,-1,0
  4140.1    0.05       0  4985.5    0.05       0  5010.1    0.05       0
Bank Sta=4985.5,5010.1
Exp/Cntr=0.3,0.1

Type RM Length L Ch R = 1,1065158,416,416,416
BEGIN DESCRIPTION:
Mapping XS 9e2504b2
END DESCRIPTION:
XS GIS Cut Line= 3
      1304492.04      6951397.50      1304832.97      6950898.11
      1305116.20      6950542.87
#Sta/Elev= 30
  4383.3 2133.92  4500.8 2132.68  4536.7 2131.24  4614.5 2123.77  4650.4 2122.38
  4773.0 2122.14  4830.7 2123.62  4867.0 2120.00  4874.7 2115.79  4880.7 2117.12
  4889.6 2121.56  4952.5 2121.21  4961.4 2119.73  4976.0 2114.09  4979.6 2111.39
  4981.6 2109.39  5002.2 2109.39  5004.2 2111.39  5017.7 2118.73  5032.1 2121.56
  5046.5 2122.30  5110.6 2121.46  5117.0 2119.31  5139.4 2116.90  5153.8 2120.31
  5181.0 2120.69  5189.0 2121.62  5217.9 2130.45  5238.7 2131.04  5442.3 2129.29
#Mann=3,-1,0
  4383.3    0.05       0  4979.6    0.05       0  5004.2    0.05       0
Bank Sta=4979.6,5004.2
Exp/Cntr=0.3,0.1

Type RM Length L Ch R = 1,1064742,1011,1011,1011
BEGIN DESCRIPTION:
Mapping XS 862a7fed
END DESCRIPTION:
XS GIS Cut Line= 2
      1304755.98      6951762.34      1305303.95      6950922.51
#Sta/Elev= 30
  4298.3 2145.15  4307.6 2145.57  4322.7 2144.07  4380.0 2142.55  4431.3 2139.31
  4554.2 2134.87  4690.8 2126.84  4711.8 2124.87  4793.0 2123.95  4814.5 2125.28
  4820.5 2124.79  4835.6 2126.48  4871.8 2126.20  4914.0 2118.48  4936.3 2119.89
  4959.4 2118.69  4980.4 2114.32  4985.7 2110.92  4987.7 2108.92  5008.8 2108.92
  5010.8 2110.92  5022.6 2117.78  5037.7 2120.25  5089.1 2121.50  5095.0 2122.23
  5103.5 2125.18  5139.3 2128.50  5175.1 2129.22  5197.7 2128.17  5301.1 2128.43
#Mann=3,-1,0
  4298.3    0.05       0  4985.7    0.05       0  5010.8    0.05       0
Bank Sta=4985.7,5010.8
Exp/Cntr=0.3,0.1

Type RM Length L Ch R = 1,1063731,1337,1337,1337
BEGIN DESCRIPTION:
Mapping XS 083b31eb
END DESCRIPTION:
XS GIS Cut Line= 2
      1306421.95      6952647.21      1305477.94      6950856.85
#Sta/Elev= 30
  3911.7 2172.30  4235.2 2176.29  4367.4 2172.26  4405.8 2173.54  4419.5 2170.78
  4427.8 2172.34  4433.5 2168.12  4449.8 2171.25  4455.5 2166.94  4471.9 2168.38
  4477.5 2163.47  4493.9 2163.96  4499.5 2160.40  4510.0 2160.22  4537.9 2153.81
  4840.6 2137.94  4923.1 2122.02  4961.5 2117.64  4996.1 2116.91  5005.5 2114.05
  5005.7 2109.33  5008.5 2108.33  5040.8 2109.33  5055.2 2109.24  5071.6 2114.94
  5077.3 2112.91  5093.6 2118.08  5165.7 2118.24  5278.7 2125.09  5935.7 2127.89
#Mann=3,-1,0
  3911.7    0.05       0  5005.7    0.05       0  5040.8    0.05       0
Bank Sta=5005.7,5040.8
Exp/Cntr=0.3,0.1

Type RM Length L Ch R = 1,1062394,838,838,838
BEGIN DESCRIPTION:
Mapping XS 12e07aba
END DESCRIPTION:
XS GIS Cut Line= 3
      1306965.32      6951455.20      1306299.09      6950649.07
      1305599.75      6950875.52
#Sta/Elev= 30
  3847.6 2149.20  4087.7 2137.21  4108.5 2137.49  4307.8 2129.79  4378.2 2129.71
  4392.5 2127.53  4449.8 2128.01  4499.3 2126.21  4584.0 2125.77  4740.3 2121.72
  4950.3 2120.66  4960.8 2119.57  4973.8 2114.08  4981.8 2112.97  4987.5 2104.83
  4989.5 2103.83  5010.6 2103.83  5012.6 2104.83  5013.3 2109.42  5032.6 2110.32
  5044.9 2113.51  5086.9 2115.77  5128.6 2113.55  5165.8 2115.56  5223.6 2115.75
  5261.8 2117.27  5318.2 2122.53  5538.9 2121.84  5587.0 2122.45  5628.5 2124.46
#Mann=3,-1,0
  3847.6    0.05       0  4987.5    0.05       0  5012.6    0.05       0
Bank Sta=4987.5,5012.6
Exp/Cntr=0.3,0.1

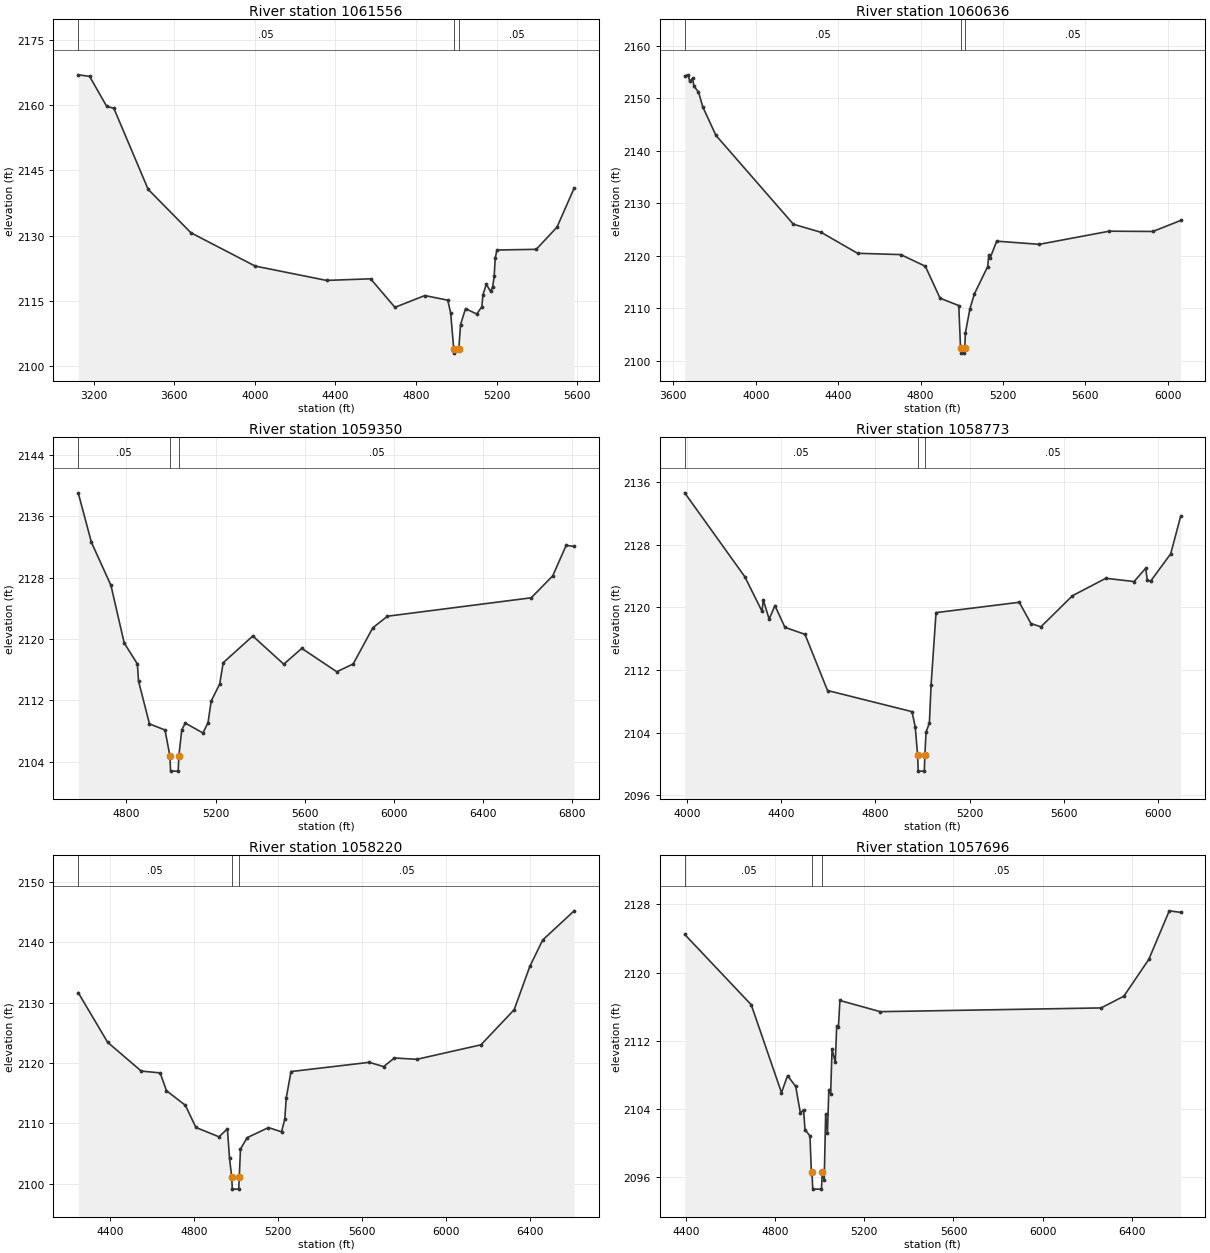
Type RM Length L Ch R = 1,1061556,920,920,920
BEGIN DESCRIPTION:
Clear Fork Brazos Rv 334.0
END DESCRIPTION:
XS GIS Cut Line= 3
      1307154.97      6951487.97      1305905.00      6950088.00
      1305705.01      6949538.03
#Sta/Elev= 30
  3123.2 2166.99  3179.6 2166.64  3264.9 2159.72  3300.0 2159.31  3470.5 2140.66
  3682.9 2130.67  4001.4 2123.02  4355.8 2119.72  4574.9 2120.09  4695.3 2113.53
  4844.1 2116.24  4957.8 2115.17  4972.0 2112.27  4987.4 2104.00  4989.4 2103.00
  5012.6 2104.00  5021.3 2109.57  5045.9 2113.23  5101.7 2111.99  5127.0 2113.67
  5132.3 2116.37  5149.0 2118.85  5170.2 2117.18  5180.9 2118.29  5188.2 2120.66
  5193.5 2124.92  5202.2 2126.71  5397.0 2126.87  5500.1 2131.97  5585.2 2140.95
#Mann=3,-1,0
  3123.2    0.05       0  4987.4    0.05       0  5012.6    0.05       0
Bank Sta=4987.4,5012.6
Exp/Cntr=0.3,0.1

Type RM Length L Ch R = 1,1060636,1286,1286,1286
BEGIN DESCRIPTION:
Mapping XS c933e62d
END DESCRIPTION:
XS GIS Cut Line= 4
      1307198.51      6951248.67      1306419.01      6950575.78
      1306645.54      6950029.45      1306079.63      6949483.52
#Sta/Elev= 30
  3654.7 2154.24  3672.3 2154.44  3678.9 2153.20  3693.2 2153.75  3699.8 2152.26
  3721.7 2151.18  3742.5 2148.34  3806.2 2142.92  4182.4 2125.98  4317.3 2124.43
  4494.0 2120.44  4703.7 2120.19  4822.9 2117.97  4894.5 2111.88  4985.2 2110.48
  4993.9 2102.42  4995.5 2101.42  5012.5 2101.42  5014.1 2102.42  5017.6 2105.30
  5039.3 2109.85  5060.9 2112.69  5125.7 2117.92  5131.1 2120.18  5136.7 2119.45
  5169.2 2122.75  5376.2 2122.15  5715.8 2124.65  5928.0 2124.60  6062.2 2126.69
#Mann=3,-1,0
  3654.7    0.05       0  4993.9    0.05       0  5014.1    0.05       0
Bank Sta=4993.9,5014.1
Exp/Cntr=0.3,0.1

Type RM Length L Ch R = 1,1059350,577,577,577
BEGIN DESCRIPTION:
Clear Fork Brazos Rv 333.0
END DESCRIPTION:
XS GIS Cut Line= 3
      1307704.99      6950587.96      1307605.00      6950188.00
      1306005.03      6949338.01
#Sta/Elev= 30
  4583.5 2139.06  4642.7 2132.61  4730.3 2127.00  4789.6 2119.50  4848.9 2116.75
  4854.0 2114.52  4903.0 2108.95  4972.6 2108.15  4994.6 2104.79  4997.8 2102.79
  5031.7 2102.79  5034.9 2104.79  5047.9 2108.17  5063.7 2109.05  5143.0 2107.76
  5165.6 2109.10  5179.8 2111.92  5218.1 2114.15  5233.6 2116.92  5366.3 2120.40
  5505.3 2116.73  5586.1 2118.79  5743.1 2115.74  5816.6 2116.76  5904.5 2121.47
  5970.4 2122.98  6615.0 2125.38  6711.4 2128.24  6771.7 2132.22  6807.5 2132.07
#Mann=3,-1,0
  4583.5    0.05       0  4994.6    0.03       0  5034.9    0.05       0
Bank Sta=4994.6,5034.9
Exp/Cntr=0.3,0.1

Type RM Length L Ch R = 1,1058773,553,553,553
BEGIN DESCRIPTION:
Clear Fork Brazos Rv 332.0
END DESCRIPTION:
XS GIS Cut Line= 3
      1308055.01      6950588.03      1307705.00      6949638.00
      1306905.03      6948888.03
#Sta/Elev= 30
  3988.7 2134.61  4244.5 2123.90  4317.6 2119.49  4322.9 2120.94  4348.0 2118.49
  4372.4 2120.22  4415.0 2117.44  4500.3 2116.55  4596.2 2109.38  4955.5 2106.68
  4969.2 2104.72  4979.4 2101.09  4981.8 2099.09  5007.7 2099.09  5010.1 2101.09
  5015.1 2104.07  5029.3 2105.22  5036.6 2110.10  5057.6 2119.32  5411.7 2120.64
  5461.0 2117.93  5503.5 2117.51  5637.9 2121.48  5779.5 2123.70  5899.7 2123.29
  5949.0 2124.98  5956.3 2123.44  5970.5 2123.35  6055.5 2126.83  6097.7 2131.60
#Mann=3,-1,0
  3988.7    0.05       0  4979.4    0.03       0  5010.1    0.05       0
Bank Sta=4979.4,5010.1
Exp/Cntr=0.3,0.1

Type RM Length L Ch R = 1,1058220,524,524,524
BEGIN DESCRIPTION:
Clear Fork Brazos Rv 331.0
END DESCRIPTION:
XS GIS Cut Line= 3
      1308105.00      6950487.95      1308105.00      6949738.00
      1307404.99      6948287.98
#Sta/Elev= 30
  4249.3 2131.64  4389.3 2123.41  4549.3 2118.64  4639.3 2118.34  4669.3 2115.39
  4759.3 2112.97  4809.3 2109.30  4919.3 2107.75  4959.3 2109.07  4969.3 2104.19
  4979.8 2101.08  4982.6 2099.08  5013.0 2099.08  5015.8 2101.08  5021.5 2105.72
  5053.0 2107.60  5154.7 2109.28  5216.8 2108.57  5232.4 2110.68  5239.4 2114.22
  5262.0 2118.56  5634.8 2120.09  5702.6 2119.38  5754.3 2120.81  5860.8 2120.59
  6165.8 2122.99  6324.0 2128.81  6398.4 2135.98  6459.7 2140.36  6609.4 2145.19
#Mann=3,-1,0
  4249.3    0.05       0  4979.8    0.05       0  5015.8    0.05       0
Bank Sta=4979.8,5015.8
Exp/Cntr=0.3,0.1

Type RM Length L Ch R = 1,1057696,616,616,616
BEGIN DESCRIPTION:
Clear Fork Brazos Rv 330.0
END DESCRIPTION:
XS GIS Cut Line= 3
      1308121.39      6950374.29      1308565.82      6949832.64
      1308855.00      6948338.00
#Sta/Elev= 30
  4395.3 2124.48  4693.6 2116.23  4829.2 2105.93  4856.5 2107.93  4893.0 2106.65
  4913.9 2103.53  4928.2 2103.92  4934.7 2101.58  4956.9 2100.86  4963.4 2096.44
  4965.8 2096.62  4969.4 2094.62  5008.5 2094.62  5012.1 2096.62  5020.8 2095.72
  5027.2 2103.40  5035.1 2101.23  5041.6 2106.29  5049.5 2105.79  5055.9 2111.01
  5070.3 2109.48  5076.8 2113.75  5084.6 2113.68  5091.1 2116.73  5272.3 2115.42
  6261.8 2115.86  6363.7 2117.23  6475.7 2121.55  6567.4 2127.24  6618.3 2127.06
#Mann=3,-1,0
  4395.3    0.05       0  4965.8    0.05       0  5012.1    0.05       0
Bank Sta=4965.8,5012.1
Exp/Cntr=0.3,0.1

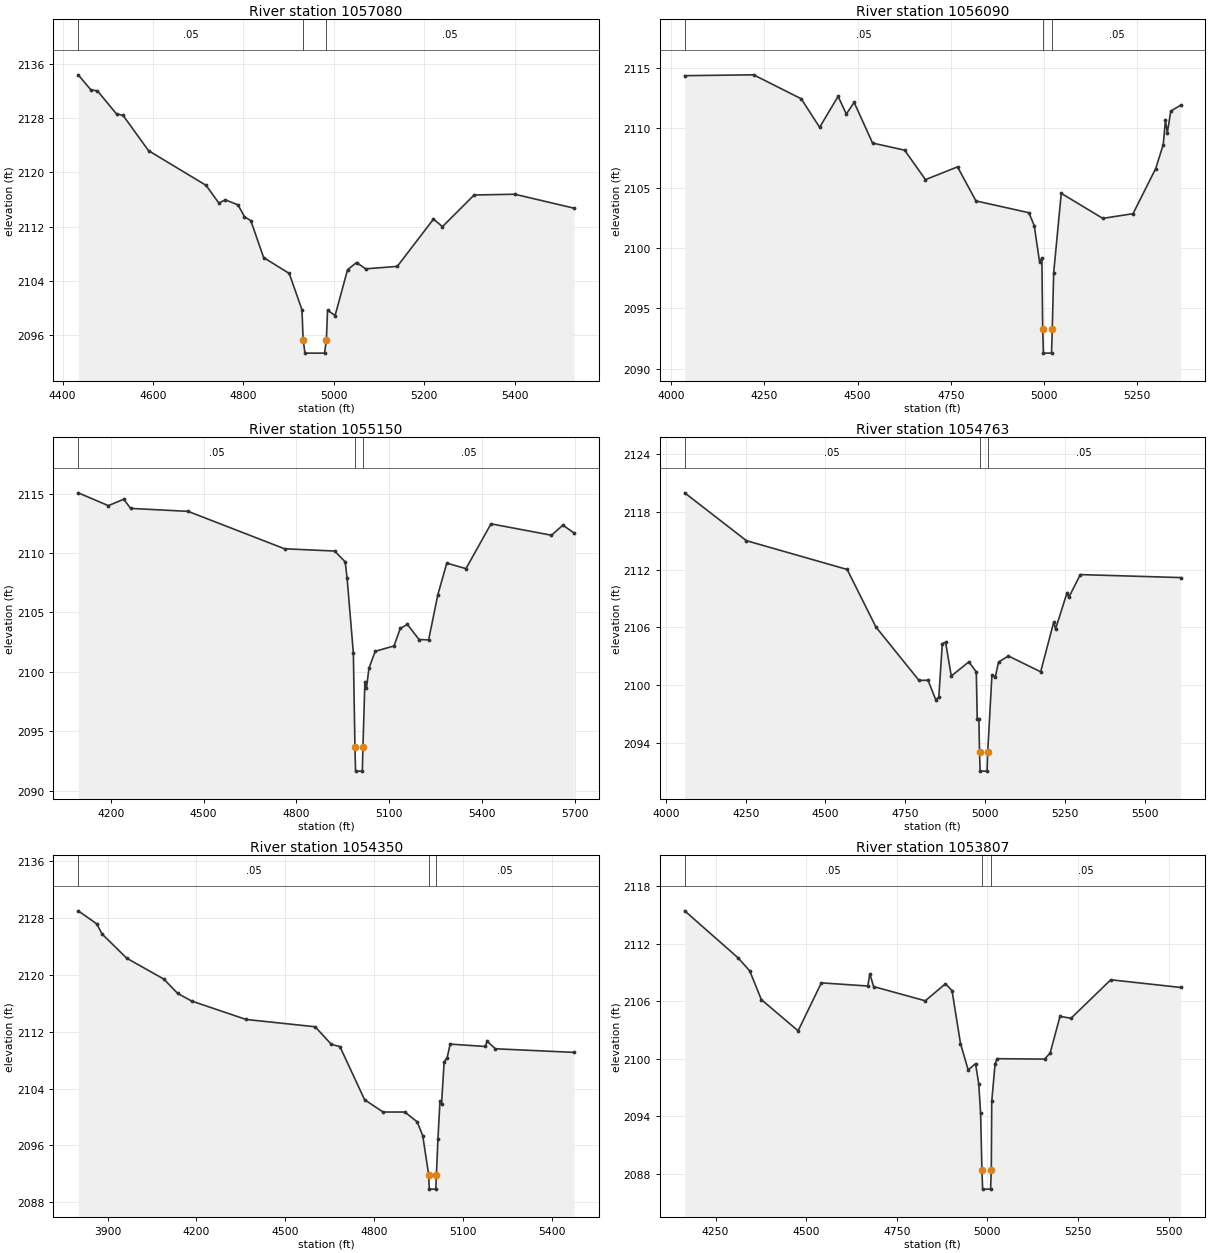
Type RM Length L Ch R = 1,1057080,990,990,990
BEGIN DESCRIPTION:
Clear Fork Brazos Rv 329.0
END DESCRIPTION:
XS GIS Cut Line= 3
      1308505.02      6950587.98      1308905.00      6950188.00
      1308905.00      6949656.75
#Sta/Elev= 30
  4434.7 2134.38  4462.9 2132.15  4477.1 2132.03  4519.5 2128.60  4533.7 2128.42
  4590.2 2123.20  4717.5 2118.08  4745.8 2115.47  4759.9 2115.95  4788.2 2115.20
  4802.4 2113.46  4816.5 2112.87  4844.8 2107.43  4901.4 2105.09  4929.6 2099.74
  4932.2 2095.34  4936.2 2093.34  4979.6 2093.34  4983.6 2095.34  4986.2 2099.67
  5002.9 2098.88  5030.4 2105.64  5050.4 2106.70  5070.4 2105.77  5140.4 2106.13
  5220.4 2113.10  5240.4 2112.00  5310.4 2116.66  5400.4 2116.77  5531.6 2114.71
#Mann=3,-1,0
  4434.7    0.05       0  4932.2    0.05       0  4983.6    0.05       0
Bank Sta=4932.2,4983.6
Exp/Cntr=0.3,0.1

Type RM Length L Ch R = 1,1056090,940,940,940
BEGIN DESCRIPTION:
Clear Fork Brazos Rv 328.0
END DESCRIPTION:
XS GIS Cut Line= 3
      1309190.82      6950784.03      1309807.48      6950043.45
      1309866.42      6949682.03
#Sta/Elev= 30
  4036.3 2114.35  4221.2 2114.42  4348.8 2112.43  4398.2 2110.06  4447.7 2112.63
  4469.8 2111.16  4490.7 2112.13  4540.1 2108.75  4626.0 2108.16  4682.0 2105.71
  4767.9 2106.77  4817.4 2103.94  4959.3 2102.96  4973.6 2101.89  4987.9 2098.89
  4994.2 2099.18  4996.3 2093.29  4998.3 2091.29  5020.0 2091.29  5022.0 2093.29
  5025.8 2097.97  5046.1 2104.57  5157.5 2102.49  5238.6 2102.88  5299.4 2106.63
  5319.6 2108.62  5325.5 2110.63  5330.6 2109.62  5339.9 2111.41  5366.2 2111.89
#Mann=3,-1,0
  4036.3    0.05       0  4996.3    0.05       0  5022.0    0.05       0
Bank Sta=4996.3,5022
Exp/Cntr=0.3,0.1

Type RM Length L Ch R = 1,1055150,387,387,387
BEGIN DESCRIPTION:
Mapping XS d27c41ea
END DESCRIPTION:
XS GIS Cut Line= 3
      1309496.39      6951485.41      1309968.60      6951138.19
      1310121.25      6950132.13
#Sta/Elev= 30
  4094.4 2115.07  4192.0 2113.99  4241.6 2114.53  4263.8 2113.76  4449.7 2113.51
  4761.6 2110.36  4923.5 2110.17  4957.7 2109.26  4963.9 2107.88  4984.1 2101.59
  4989.3 2093.64  4991.3 2091.64  5013.1 2091.64  5015.1 2093.64  5021.4 2099.17
  5026.4 2098.60  5034.7 2100.32  5055.0 2101.73  5115.6 2102.18  5135.9 2103.66
  5158.8 2103.99  5196.6 2102.72  5227.5 2102.69  5257.2 2106.48  5286.2 2109.15
  5348.3 2108.69  5429.2 2112.46  5624.8 2111.50  5661.8 2112.35  5698.1 2111.68
#Mann=3,-1,0
  4094.4    0.05       0  4989.3    0.05       0  5015.1    0.05       0
Bank Sta=4989.3,5015.1
Exp/Cntr=0.3,0.1

Type RM Length L Ch R = 1,1054763,413,413,413
BEGIN DESCRIPTION:
Clear Fork Brazos Rv 327.0
END DESCRIPTION:
XS GIS Cut Line= 3
      1310628.31      6951624.27      1310378.32      6950742.36
      1310225.55      6950124.32
#Sta/Elev= 30
  4059.0 2119.95  4252.6 2114.99  4567.9 2112.01  4658.0 2106.05  4793.1 2100.51
  4821.0 2100.54  4845.1 2098.54  4854.9 2098.77  4865.9 2104.33  4876.2 2104.47
  4894.0 2100.97  4949.0 2102.44  4972.3 2101.40  4975.3 2096.56  4980.5 2096.56
  4982.4 2093.12  4984.4 2091.12  5006.1 2091.12  5008.1 2093.12  5021.4 2101.10
  5031.7 2100.85  5042.0 2102.42  5072.9 2103.05  5173.9 2101.41  5215.3 2106.60
  5220.5 2105.83  5256.8 2109.62  5261.9 2109.11  5298.2 2111.48  5612.3 2111.17
#Mann=3,-1,0
  4059.0    0.05       0  4982.4    0.05       0  5008.1    0.05       0
Bank Sta=4982.4,5008.1
Exp/Cntr=0.3,0.1

Type RM Length L Ch R = 1,1054350,543,543,543
BEGIN DESCRIPTION:
Clear Fork Brazos Rv 326.0
END DESCRIPTION:
XS GIS Cut Line= 3
      1310989.44      6951659.03      1310705.00      6950488.00
      1310579.85      6950034.53
#Sta/Elev= 30
  3800.6 2129.04  3863.4 2127.20  3880.9 2125.79  3964.4 2122.37  4089.7 2119.43
  4136.6 2117.41  4183.5 2116.34  4367.6 2113.74  4601.2 2112.71  4655.8 2110.23
  4684.7 2109.92  4768.2 2102.43  4830.7 2100.70  4903.8 2100.70  4945.6 2099.33
  4964.5 2097.38  4984.7 2091.84  4986.7 2089.84  5008.7 2089.84  5010.7 2091.84
  5016.0 2096.96  5022.9 2102.28  5028.0 2101.79  5036.8 2107.72  5047.2 2108.38
  5057.2 2110.27  5175.8 2109.93  5182.0 2110.67  5210.2 2109.61  5476.1 2109.10
#Mann=3,-1,0
  3800.6    0.05       0  4984.7    0.05       0  5010.7    0.05       0
Bank Sta=4984.7,5010.7
Exp/Cntr=0.3,0.1

Type RM Length L Ch R = 1,1053807,537,537,537
BEGIN DESCRIPTION:
Clear Fork Brazos Rv 325.0
END DESCRIPTION:
XS GIS Cut Line= 4
      1311084.97      6951234.26      1311268.27      6950666.06
      1311205.00      6950438.00      1310920.02      6949985.47
#Sta/Elev= 30
  4164.9 2115.44  4312.5 2110.53  4344.5 2109.17  4376.5 2106.18  4477.9 2102.93
  4542.0 2107.93  4670.2 2107.60  4675.8 2108.88  4686.3 2107.54  4828.8 2106.06
  4884.5 2107.83  4902.6 2107.13  4926.0 2101.60  4947.2 2098.85  4967.5 2099.50
  4976.3 2097.41  4981.5 2094.32  4985.1 2088.42  4987.1 2086.42  5009.0 2086.42
  5011.0 2088.42  5012.2 2095.56  5021.5 2099.51  5027.5 2100.02  5158.1 2099.98
  5173.4 2100.61  5200.5 2104.43  5231.1 2104.24  5340.6 2108.25  5533.4 2107.45
#Mann=3,-1,0
  4164.9    0.05       0  4985.1    0.03       0  5011.0    0.05       0
Bank Sta=4985.1,5011
Exp/Cntr=0.3,0.1