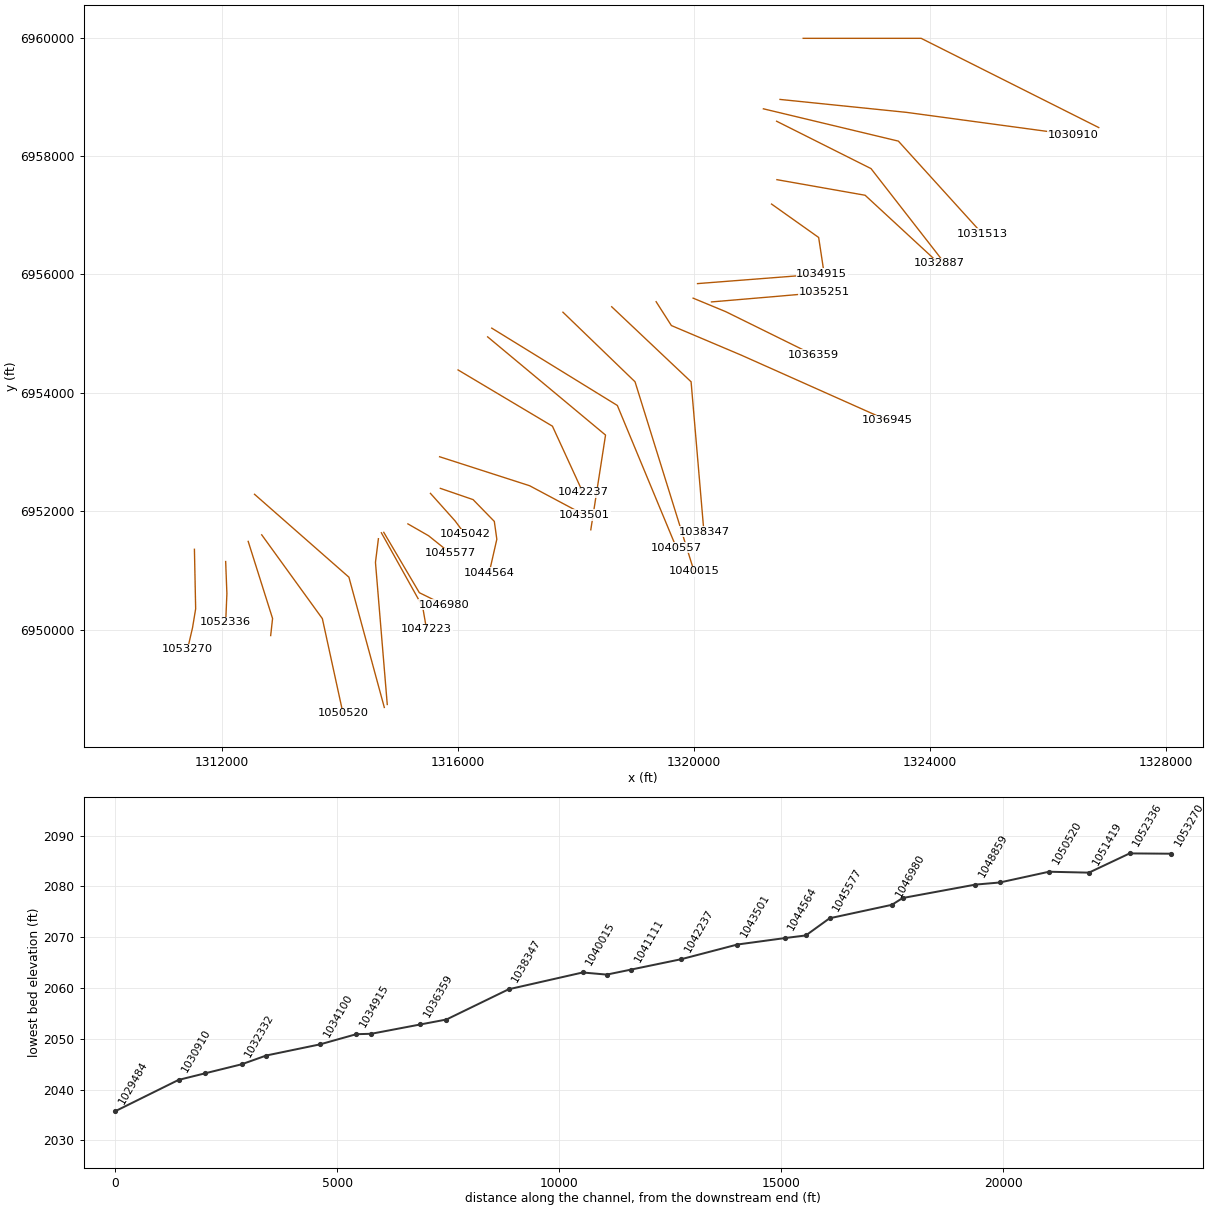
HEC-RAS study Clear Fork Brazos Rv.prj: Clear Fork Brazos Rv Base Level Engineering

--- Clear Fork Brazos Rv.g01 (geometry) --- (continued)

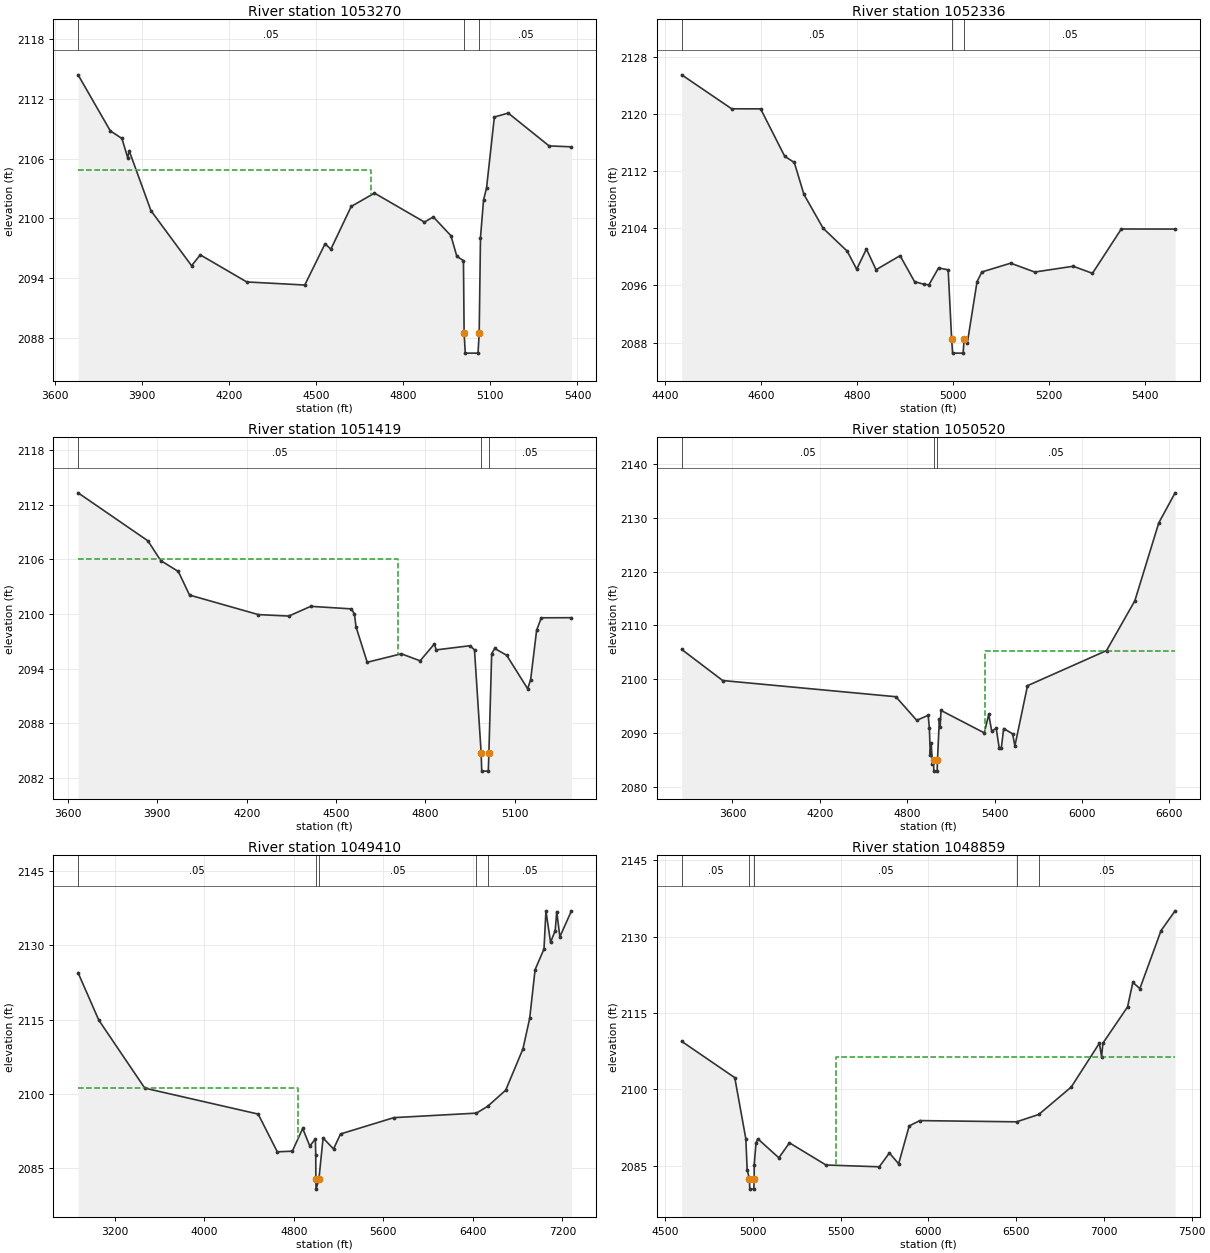
Type RM Length L Ch R = 1,1053270,934,934,934
BEGIN DESCRIPTION:
Clear Fork Brazos Rv 324.0
END DESCRIPTION:
XS GIS Cut Line= 4
      1311536.35      6951359.04      1311557.21      6950354.44
      1311505.00      6950038.00      1311420.01      6949673.00
#Sta/Elev= 30
  3679.0 2114.41  3790.1 2108.78  3830.1 2108.02  3850.0 2106.08  3855.0 2106.79
  3930.1 2100.77  4070.1 2095.24  4100.1 2096.33  4260.2 2093.61  4460.2 2093.30
  4530.2 2097.44  4550.2 2096.90  4620.2 2101.19  4700.5 2102.53  4872.8 2099.62
  4903.2 2100.14  4964.0 2098.25  4984.3 2096.18  5007.1 2095.75  5009.4 2088.46
  5013.4 2086.46  5057.3 2086.46  5061.3 2088.46  5065.8 2098.07  5076.4 2101.85
  5086.7 2103.05  5113.6 2110.17  5161.3 2110.57  5302.3 2107.27  5379.3 2107.18
#Mann=3,-1,0
  3679.0    0.05       0  5009.4    0.03       0  5061.3    0.05       0
#XS Ineff=2,0
    0.00 4687.50 2104.81 5312.50    0.00 2104.81
Permanent Ineff=
       F       F
Bank Sta=5009.4,5061.3
Exp/Cntr=0.3,0.1

Type RM Length L Ch R = 1,1052336,917,917,917
BEGIN DESCRIPTION:
Clear Fork Brazos Rv 323.0
END DESCRIPTION:
XS GIS Cut Line= 3
      1312065.82      6951152.10      1312086.66      6950610.42
      1312066.40      6950126.12
#Sta/Elev= 30
  4435.1 2125.44  4539.0 2120.69  4599.3 2120.68  4649.4 2114.05  4669.4 2113.18
  4689.4 2108.72  4729.4 2103.98  4779.5 2100.78  4799.2 2098.26  4819.5 2101.08
  4839.5 2098.18  4889.5 2100.15  4919.6 2096.52  4939.6 2096.14  4949.6 2096.08
  4969.6 2098.43  4989.6 2098.17  4996.8 2088.52  4998.8 2086.52  5020.8 2086.52
  5022.8 2088.52  5029.6 2088.00  5049.7 2096.51  5059.7 2097.87  5119.7 2099.10
  5169.8 2097.86  5249.8 2098.67  5289.9 2097.68  5349.9 2103.88  5461.9 2103.87
#Mann=3,-1,0
  4435.1    0.05       0  4996.8    0.05       0  5022.8    0.05       0
Bank Sta=4996.8,5022.8
Exp/Cntr=0.3,0.1

Type RM Length L Ch R = 1,1051419,899,899,899
BEGIN DESCRIPTION:
Clear Fork Brazos Rv 322.0
END DESCRIPTION:
XS GIS Cut Line= 3
      1312447.76      6951492.39      1312860.94      6950190.27
      1312828.87      6949901.85
#Sta/Elev= 30
  3633.9 2113.33  3868.4 2108.05  3911.3 2105.88  3970.5 2104.68  4008.0 2102.09
  4239.1 2099.94  4341.4 2099.78  4414.9 2100.85  4551.3 2100.57  4561.7 2100.00
  4567.0 2098.59  4604.5 2094.70  4719.1 2095.63  4782.1 2094.86  4830.4 2096.73
  4835.7 2096.06  4949.9 2096.52  4964.7 2096.06  4987.0 2084.73  4989.0 2082.73
  5011.0 2082.73  5013.0 2084.73  5022.4 2095.65  5032.5 2096.22  5072.7 2095.47
  5143.1 2091.79  5153.2 2092.79  5173.3 2098.23  5189.0 2099.59  5290.2 2099.60
#Mann=3,-1,0
  3633.9    0.05       0  4987.0    0.05       0  5013.0    0.05       0
#XS Ineff=2,0
    0.00 4709.00 2106.08 5291.00    0.00 2106.08
Permanent Ineff=
       F       F
Bank Sta=4987,5013
Exp/Cntr=0.3,0.1

Type RM Length L Ch R = 1,1050520,1110,1110,1110
BEGIN DESCRIPTION:
Clear Fork Brazos Rv 321.0
END DESCRIPTION:
XS GIS Cut Line= 3
      1312676.94      6951603.46      1313705.00      6950188.00
      1314054.99      6948588.04
#Sta/Elev= 30
  3251.7 2105.53  3532.9 2099.75  4721.7 2096.74  4865.2 2092.35  4943.5 2093.29
  4951.7 2090.98  4958.2 2085.92  4964.4 2088.07  4972.9 2084.30  4980.3 2084.91
  4982.3 2082.91  5005.3 2082.91  5007.3 2084.91  5020.5 2092.52  5025.6 2091.02
  5031.8 2094.19  5328.7 2090.02  5359.4 2093.45  5379.9 2090.33  5410.6 2090.87
  5431.0 2087.28  5446.0 2087.26  5461.8 2090.83  5523.2 2089.85  5538.9 2087.59
  5625.5 2098.79  6168.1 2105.32  6362.6 2114.58  6526.7 2129.05  6638.9 2134.64
#Mann=3,-1,0
  3251.7    0.05       0  4980.3    0.05       0  5007.3    0.05       0
#XS Ineff=2,0
       0                 5330.70    0.00 2105.23
Permanent Ineff=
       F       F
Bank Sta=4980.3,5007.3
Exp/Cntr=0.3,0.1

Type RM Length L Ch R = 1,1049410,551,551,551
BEGIN DESCRIPTION:
Clear Fork Brazos Rv 320.0
END DESCRIPTION:
XS GIS Cut Line= 3
      1312554.99      6952288.01      1314155.00      6950888.00
      1314755.00      6948687.99
#Sta/Elev= 30
  2874.2 2124.49  3058.8 2114.94  3469.8 2101.19  4482.5 2095.95  4653.3 2088.33
  4787.6 2088.45  4880.2 2093.05  4943.8 2089.49  4993.1 2090.92  4996.9 2087.72
  4997.8 2082.79  4999.8 2080.79  5024.9 2082.79  5062.4 2091.12  5155.7 2088.90
  5217.9 2091.93  5694.7 2095.23  6432.0 2096.14  6532.7 2097.53  6693.2 2100.77
  6847.0 2109.10  6907.4 2115.26  6955.8 2125.12  7035.3 2129.29  7052.6 2136.96
  7094.0 2130.64  7135.5 2133.00  7149.3 2136.86  7176.9 2131.75  7280.6 2137.00
#Mann=5,-1,0
  2874.2    0.05       0  4997.8    0.05       0  5024.9    0.05       0
  6432.0    0.12       0  6532.7    0.05       0
#XS Ineff=2,0
    0.00 4834.30 2101.29               0
Permanent Ineff=
       F       F
Bank Sta=4997.8,5024.9
Exp/Cntr=0.3,0.1

Type RM Length L Ch R = 1,1048859,1636,1636,1636
BEGIN DESCRIPTION:
Clear Fork Brazos Rv 319.0
END DESCRIPTION:
XS GIS Cut Line= 3
      1314655.00      6951538.00      1314605.00      6951138.00
      1314805.00      6948738.03
#Sta/Elev= 30
  4594.3 2109.41  4896.6 2102.28  4959.6 2090.26  4967.2 2084.20  4980.1 2082.37
  4982.1 2080.37  5005.2 2080.37  5007.2 2082.37  5007.4 2085.14  5017.5 2089.41
  5027.5 2090.27  5147.9 2086.52  5208.1 2089.47  5416.4 2085.11  5719.9 2084.76
  5777.6 2087.48  5830.3 2085.35  5890.5 2092.79  5950.7 2093.84  6502.3 2093.60
  6628.6 2095.04  6813.7 2100.43  6974.2 2109.05  6986.8 2106.41  6994.3 2109.06
  7134.8 2116.19  7164.9 2121.00  7205.0 2119.79  7325.5 2131.18  7405.7 2135.07
#Mann=5,-1,0
  4594.3    0.05       0  4980.1    0.05       0  5007.2    0.05       0
  6502.3    0.12       0  6628.6    0.05       0
#XS Ineff=2,0
       0                 5471.70    0.00 2106.29
Permanent Ineff=
       F       F
Bank Sta=4980.1,5007.2
Exp/Cntr=0.3,0.1

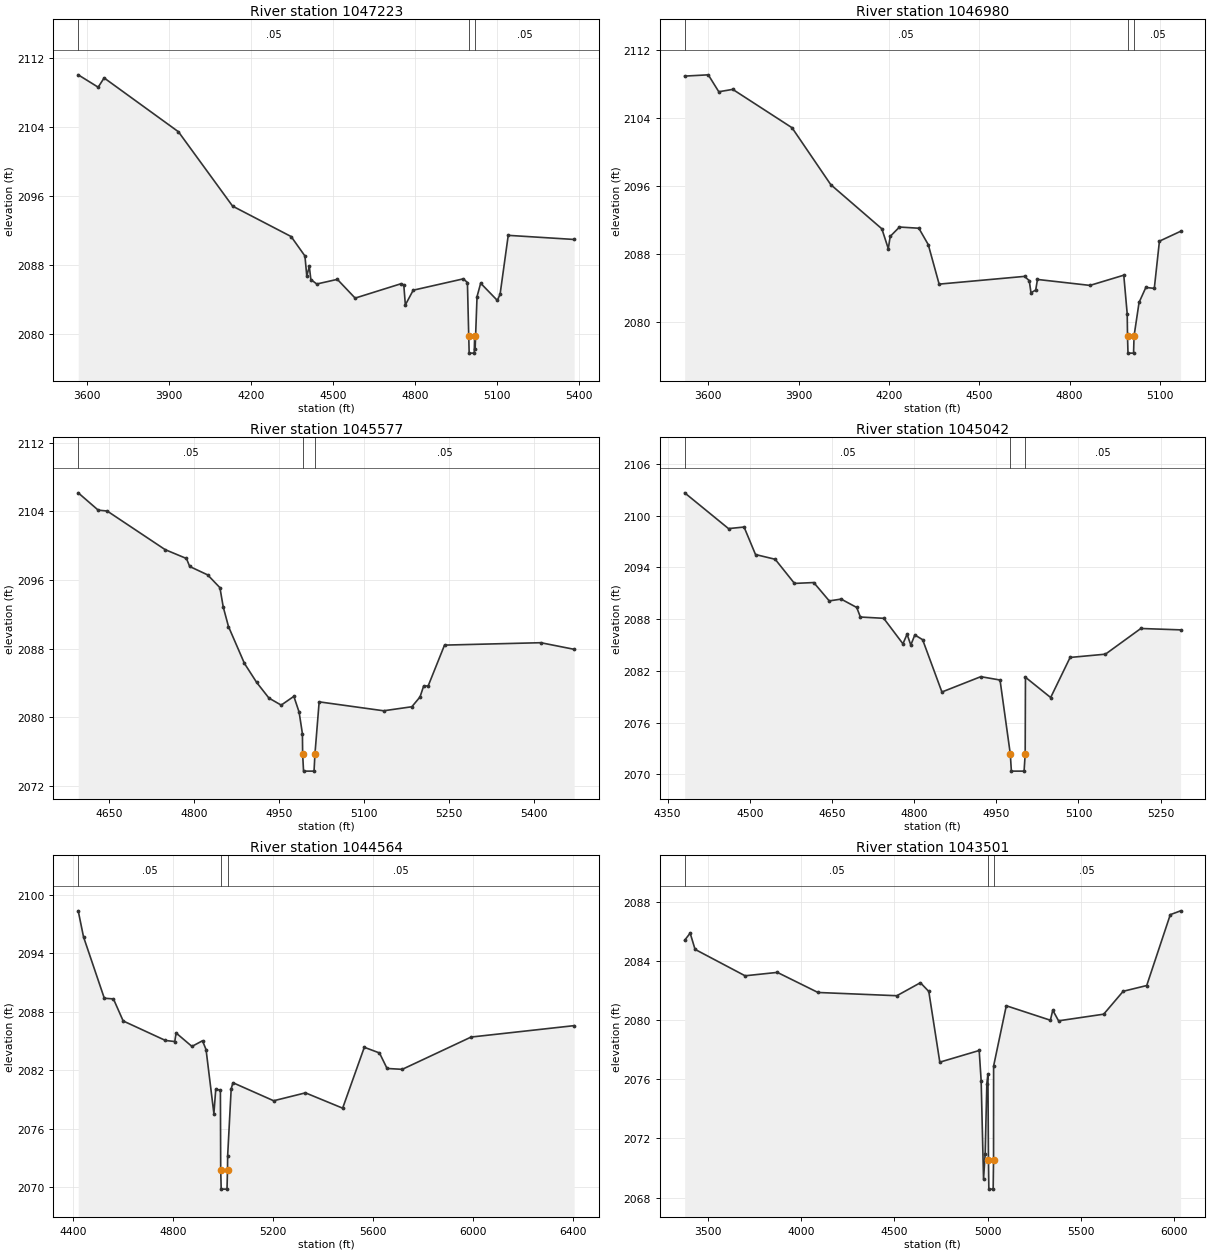
Type RM Length L Ch R = 1,1047223,243,243,243
BEGIN DESCRIPTION:
Clear Fork Brazos Rv 318.0
END DESCRIPTION:
XS GIS Cut Line= 3
      1314705.00      6951638.00      1315405.00      6950388.00
      1315470.58      6950010.91
#Sta/Elev= 30
  3568.0 2110.10  3641.1 2108.66  3662.8 2109.74  3934.8 2103.48  4133.1 2094.83
  4347.4 2091.29  4397.9 2089.03  4404.7 2086.70  4413.9 2087.82  4419.6 2086.29
  4441.3 2085.77  4516.6 2086.31  4581.7 2084.13  4749.5 2085.80  4759.8 2085.66
  4765.5 2083.34  4794.3 2085.05  4977.7 2086.37  4992.7 2085.94  4997.5 2079.73
  4999.1 2077.73  5017.6 2077.73  5019.2 2079.73  5020.9 2078.23  5027.9 2084.30
  5041.2 2085.86  5102.2 2083.86  5112.3 2084.58  5142.1 2091.43  5383.4 2090.95
#Mann=3,-1,0
  3568.0    0.05       0  4997.5    0.05       0  5019.2    0.05       0
Bank Sta=4997.5,5019.2
Exp/Cntr=0.3,0.1

Type RM Length L Ch R = 1,1046980,1403,1403,1403
BEGIN DESCRIPTION:
Mapping XS 3e9c2f5c
END DESCRIPTION:
XS GIS Cut Line= 3
      1314745.79      6951645.49      1315348.76      6950626.05
      1315764.59      6950422.70
#Sta/Elev= 30
  3521.6 2108.95  3600.0 2109.10  3634.9 2107.11  3681.3 2107.39  3878.2 2102.88
  4006.9 2096.19  4176.6 2091.00  4198.0 2088.66  4204.2 2090.11  4235.1 2091.21
  4299.4 2091.07  4330.7 2089.14  4366.8 2084.50  4650.5 2085.41  4666.1 2084.91
  4671.9 2083.48  4687.6 2083.81  4693.4 2085.05  4867.8 2084.35  4980.1 2085.55
  4991.5 2081.00  4992.5 2078.39  4994.1 2076.39  5012.6 2076.39  5014.2 2078.39
  5030.9 2082.35  5053.4 2084.11  5081.5 2084.00  5098.5 2089.55  5168.9 2090.71
#Mann=3,-1,0
  3521.6    0.05       0  4992.5    0.05       0  5014.2    0.05       0
Bank Sta=4992.5,5014.2
Exp/Cntr=0.3,0.1

Type RM Length L Ch R = 1,1045577,535,535,535
BEGIN DESCRIPTION:
Clear Fork Brazos Rv 317.0
END DESCRIPTION:
XS GIS Cut Line= 3
      1315154.99      6951788.01      1315505.00      6951588.00
      1315873.23      6951294.20
#Sta/Elev= 30
  4596.2 2106.16  4631.5 2104.14  4647.3 2104.04  4749.5 2099.54  4787.0 2098.51
  4792.7 2097.58  4824.4 2096.60  4846.0 2095.11  4851.8 2092.87  4861.1 2090.58
  4889.2 2086.29  4910.8 2084.07  4932.4 2082.25  4954.0 2081.43  4976.3 2082.45
  4985.6 2080.61  4991.4 2078.10  4991.8 2075.74  4993.4 2073.74  5011.9 2073.74
  5013.5 2075.74  5020.9 2081.81  5134.6 2080.77  5184.3 2081.24  5198.7 2082.38
  5205.1 2083.65  5213.1 2083.67  5241.9 2088.42  5411.6 2088.70  5470.4 2087.93
#Mann=3,-1,0
  4596.2    0.05       0  4991.8    0.05       0  5013.5    0.05       0
Bank Sta=4991.8,5013.5
Exp/Cntr=0.3,0.1

Type RM Length L Ch R = 1,1045042,478,478,478
BEGIN DESCRIPTION:
Clear Fork Brazos Rv 316.0
END DESCRIPTION:
XS GIS Cut Line= 3
      1315537.23      6952303.30      1315955.00      6951838.00
      1316122.92      6951614.10
#Sta/Elev= 30
  4381.2 2102.65  4461.2 2098.50  4489.6 2098.68  4510.5 2095.49  4546.4 2094.94
  4581.6 2092.14  4616.8 2092.24  4645.1 2090.11  4666.8 2090.32  4695.2 2089.35
  4701.9 2088.24  4744.5 2088.09  4779.6 2085.13  4787.1 2086.25  4793.9 2084.99
  4801.3 2086.16  4815.5 2085.61  4850.7 2079.54  4921.7 2081.32  4956.8 2080.93
  4975.5 2072.36  4977.5 2070.36  5000.7 2070.36  5002.7 2072.36  5003.2 2081.25
  5049.2 2078.90  5084.7 2083.55  5149.2 2083.93  5213.8 2086.91  5286.4 2086.75
#Mann=3,-1,0
  4381.2    0.05       0  4975.5    0.05       0  5002.7    0.05       0
Bank Sta=4975.5,5002.7
Exp/Cntr=0.3,0.1

Type RM Length L Ch R = 1,1044564,1063,1063,1063
BEGIN DESCRIPTION:
Clear Fork Brazos Rv 315.0
END DESCRIPTION:
XS GIS Cut Line= 5
      1315704.97      6952388.01      1316259.83      6952198.01
      1316619.55      6951830.06      1316662.24      6951528.98
      1316533.76      6950966.43
#Sta/Elev= 30
  4422.0 2098.36  4443.2 2095.69  4526.3 2089.40  4562.8 2089.33  4601.7 2087.07
  4770.8 2085.07  4807.9 2084.96  4813.2 2085.84  4876.5 2084.46  4918.8 2085.04
  4933.0 2084.13  4964.3 2077.57  4971.7 2080.06  4990.3 2079.98  4991.5 2071.83
  4993.5 2069.83  5016.7 2069.83  5018.7 2071.83  5019.3 2073.25  5033.4 2080.11
  5040.4 2080.74  5203.2 2078.89  5330.3 2079.70  5478.9 2078.13  5565.5 2084.37
  5626.1 2083.79  5656.4 2082.20  5717.1 2082.11  5992.3 2085.42  6404.2 2086.59
#Mann=3,-1,0
  4422.0    0.05       0  4991.5    0.05       0  5018.7    0.05       0
Bank Sta=4991.5,5018.7
Exp/Cntr=0.3,0.1

Type RM Length L Ch R = 1,1043501,1264,1264,1264
BEGIN DESCRIPTION:
Clear Fork Brazos Rv 314.0
END DESCRIPTION:
XS GIS Cut Line= 3
      1315692.09      6952921.98      1317218.17      6952432.39
      1318150.24      6951937.71
#Sta/Elev= 30
  3376.1 2085.43  3405.5 2085.91  3431.7 2084.81  3699.8 2083.02  3872.8 2083.25
  4090.5 2081.89  4513.3 2081.67  4639.4 2082.55  4684.4 2081.96  4743.4 2077.17
  4954.5 2077.96  4965.0 2075.91  4977.8 2069.25  4986.5 2070.97  4995.5 2075.71
  5001.2 2076.37  5004.2 2070.57  5006.2 2068.57  5029.4 2068.57  5031.4 2070.57
  5031.8 2076.91  5099.7 2080.99  5336.0 2080.01  5348.8 2080.69  5379.9 2079.97
  5621.8 2080.42  5726.1 2081.97  5852.3 2082.36  5978.6 2087.16  6034.0 2087.42
#Mann=3,-1,0
  3376.1    0.05       0  5004.2    0.05       0  5031.4    0.05       0
Bank Sta=5004.2,5031.4
Exp/Cntr=0.3,0.1

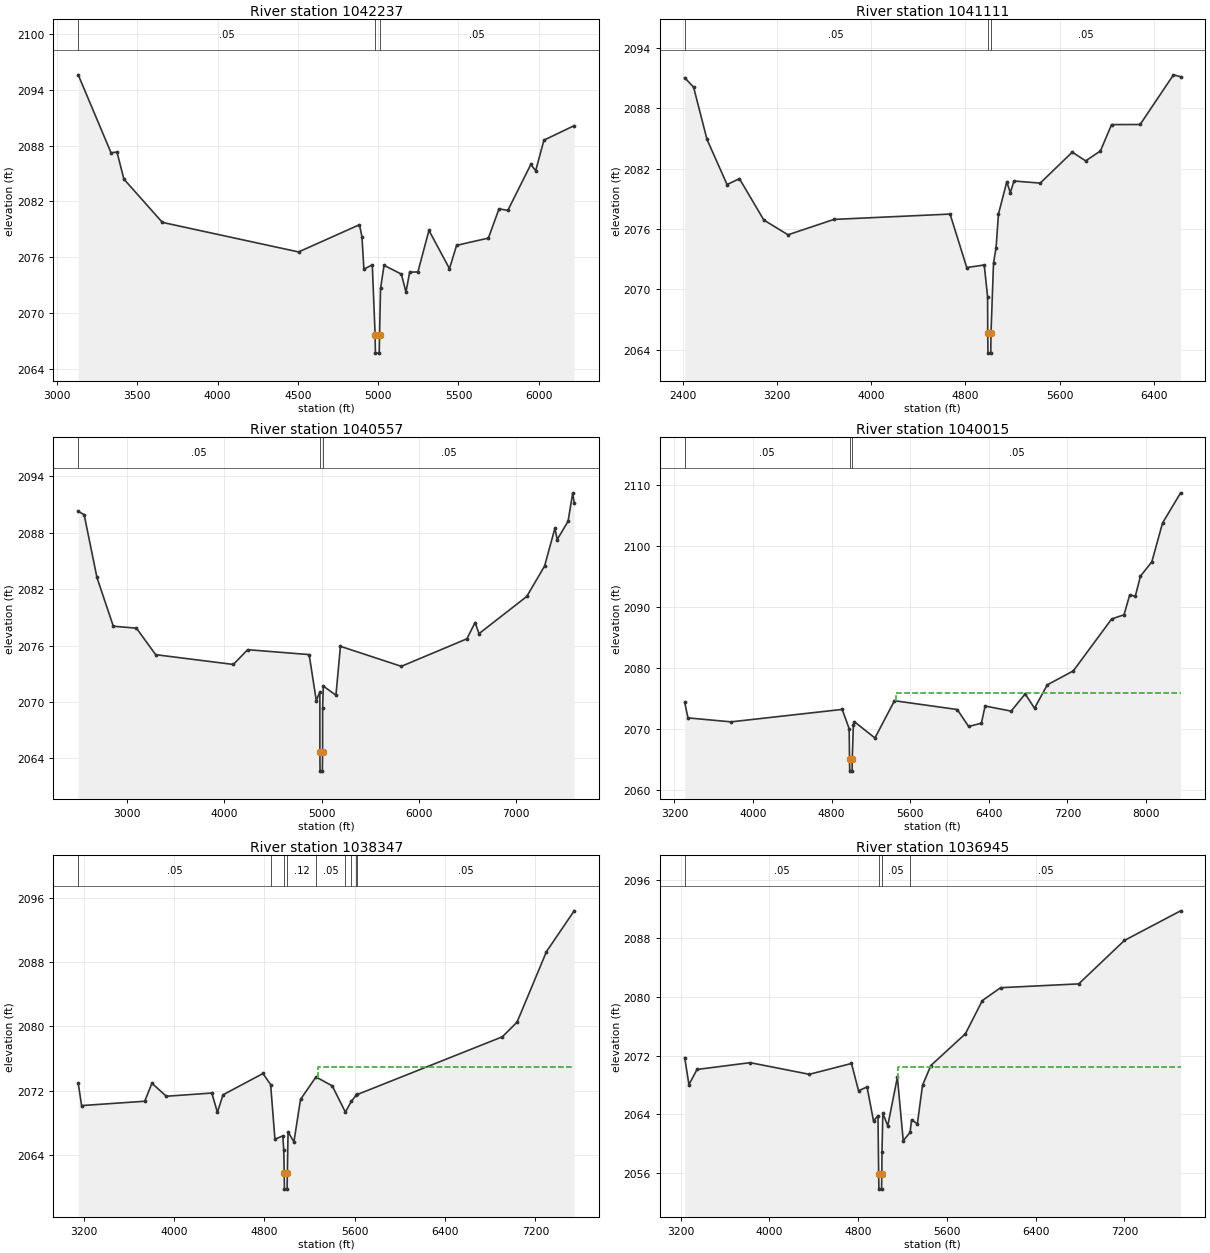
Type RM Length L Ch R = 1,1042237,1126,1126,1126
BEGIN DESCRIPTION:
Clear Fork Brazos Rv 313.0
END DESCRIPTION:
XS GIS Cut Line= 3
      1316005.04      6954387.97      1317605.00      6953438.00
      1318119.22      6952322.99
#Sta/Elev= 30
  3132.0 2095.63  3336.5 2087.24  3373.6 2087.32  3416.4 2084.41  3656.1 2079.75
  4504.3 2076.57  4883.6 2079.50  4899.2 2078.19  4911.3 2074.72  4963.5 2075.18
  4981.0 2067.68  4983.0 2065.68  5006.7 2065.68  5008.7 2067.68  5014.8 2072.65
  5036.8 2075.13  5144.7 2074.18  5173.1 2072.25  5196.1 2074.39  5247.5 2074.42
  5316.3 2078.89  5444.2 2074.77  5488.3 2077.28  5686.5 2078.06  5752.6 2081.21
  5807.6 2081.04  5950.8 2085.99  5981.0 2085.31  6032.4 2088.60  6220.6 2090.16
#Mann=3,-1,0
  3132.0    0.05       0  4981.0    0.05       0  5008.7    0.05       0
Bank Sta=4981,5008.7
Exp/Cntr=0.3,0.1

Type RM Length L Ch R = 1,1041111,554,554,554
BEGIN DESCRIPTION:
Clear Fork Brazos Rv 312.0
END DESCRIPTION:
XS GIS Cut Line= 3
      1316506.77      6954946.38      1318505.00      6953288.00
      1318255.00      6951687.97
#Sta/Elev= 30
  2413.0 2091.04  2488.7 2090.09  2602.7 2084.90  2773.3 2080.41  2878.7 2080.99
  3085.8 2076.88  3291.5 2075.41  3682.2 2076.94  4669.2 2077.47  4811.2 2072.15
  4959.6 2072.41  4988.3 2069.23  4989.4 2065.64  4991.4 2063.64  5015.2 2063.64
  5017.2 2065.64  5038.6 2072.62  5060.4 2074.13  5080.6 2077.48  5151.5 2080.68
  5181.8 2079.59  5212.2 2080.76  5435.4 2080.55  5708.1 2083.63  5822.0 2082.76
  5947.5 2083.75  6042.1 2086.37  6285.0 2086.38  6568.4 2091.32  6629.2 2091.13
#Mann=3,-1,0
  2413.0    0.05       0  4989.4    0.05       0  5017.2    0.05       0
Bank Sta=4989.4,5017.2
Exp/Cntr=0.3,0.1

Type RM Length L Ch R = 1,1040557,542,542,542
BEGIN DESCRIPTION:
Clear Fork Brazos Rv 311.0
END DESCRIPTION:
XS GIS Cut Line= 3
      1316576.27      6955093.91      1318705.00      6953788.00
      1319705.01      6951387.98
#Sta/Elev= 30
  2498.9 2090.28  2560.0 2089.92  2691.4 2083.25  2859.6 2078.06  3097.5 2077.85
  3295.2 2075.03  4093.3 2073.99  4240.2 2075.56  4872.5 2075.04  4946.0 2070.14
  4982.7 2071.08  4982.8 2064.64  4984.8 2062.64  5008.6 2062.64  5010.6 2064.64
  5010.9 2069.32  5017.9 2071.69  5147.9 2070.72  5194.0 2075.92  5820.1 2073.79
  6494.0 2076.72  6577.9 2078.45  6618.6 2077.27  7108.8 2081.22  7292.4 2084.46
  7398.6 2088.48  7422.4 2087.28  7534.0 2089.23  7581.6 2092.25  7596.3 2091.21
#Mann=3,-1,0
  2498.9    0.05       0  4982.8    0.03       0  5010.6    0.05       0
Bank Sta=4982.8,5010.6
Exp/Cntr=0.3,0.1

Type RM Length L Ch R = 1,1040015,1668,1668,1668
BEGIN DESCRIPTION:
Clear Fork Brazos Rv 310.0
END DESCRIPTION:
XS GIS Cut Line= 3
      1317782.82      6955363.04      1319005.00      6954188.00
      1320004.99      6950988.03
#Sta/Elev= 30
  3304.7 2074.34  3338.0 2071.78  3776.7 2071.13  4908.1 2073.17  4978.9 2070.01
  4982.7 2065.06  4984.7 2063.06  5008.4 2063.06  5010.4 2065.06  5021.6 2070.57
  5031.5 2071.16  5241.1 2068.49  5440.1 2074.59  6079.2 2073.15  6195.0 2070.37
  6324.9 2070.91  6362.6 2073.72  6627.7 2072.89  6770.7 2075.71  6865.5 2073.36
  6995.4 2077.19  7260.5 2079.48  7650.8 2087.98  7776.5 2088.67  7833.6 2091.87
  7891.7 2091.74  7944.1 2095.00  8059.4 2097.33  8168.9 2103.71  8352.7 2108.64
#Mann=3,-1,0
  3304.7    0.05       0  4982.7    0.05       0  5010.4    0.05       0
#XS Ineff=2,0
       0                 5454.50    0.00 2075.87
Permanent Ineff=
       F       F
Bank Sta=4982.7,5010.4
Exp/Cntr=0.3,0.1

Type RM Length L Ch R = 1,1038347,1402,1402,1402
BEGIN DESCRIPTION:
Clear Fork Brazos Rv 309.0
END DESCRIPTION:
XS GIS Cut Line= 3
      1318609.31      6955454.85      1319955.00      6954188.00
      1320172.57      6951653.90
#Sta/Elev= 30
  3150.9 2072.92  3181.0 2070.14  3739.8 2070.68  3803.7 2072.92  3930.7 2071.30
  4334.1 2071.70  4383.5 2069.30  4433.3 2071.48  4786.9 2074.13  4854.8 2072.75
  4892.9 2065.96  4962.6 2066.37  4971.0 2064.62  4975.1 2061.75  4977.1 2059.75
  5000.8 2059.75  5002.8 2061.75  5009.1 2066.89  5060.9 2065.62  5119.5 2070.91
  5256.5 2073.70  5400.6 2072.59  5516.9 2069.32  5568.7 2070.66  5615.0 2071.48
  5622.7 2071.52  6906.1 2078.69  7036.6 2080.51  7297.5 2089.29  7542.5 2094.36
#Mann=9,-1,0
  3150.9    0.05       0  4854.8    0.12       0  4975.1    0.07       0
  5002.8    0.12       0  5256.5    0.05       0  5516.9    0.12       0
  5568.7    0.05       0  5615.0    0.12       0  5622.7    0.05       0
#XS Ineff=2,0
       0                 5271.00    0.00 2074.98
Permanent Ineff=
       F       F
Bank Sta=4975.1,5002.8
Exp/Cntr=0.3,0.1

Type RM Length L Ch R = 1,1036945,586,586,586
BEGIN DESCRIPTION:
Clear Fork Brazos Rv 308.0
END DESCRIPTION:
XS GIS Cut Line= 4
      1319362.35      6955540.29      1319620.93      6955137.59
      1320805.00      6954638.00      1323277.46      6953539.34
#Sta/Elev= 30
  3236.6 2071.74  3275.1 2068.06  3347.8 2070.12  3826.3 2071.05  4360.0 2069.46
  4739.8 2070.94  4803.5 2067.21  4880.0 2067.74  4938.3 2063.10  4978.6 2063.81
  4984.8 2055.79  4986.8 2053.79  5010.9 2053.79  5012.9 2055.79  5014.7 2058.83
  5022.2 2064.14  5066.7 2062.44  5153.5 2069.07  5206.2 2060.40  5267.8 2061.53
  5281.4 2063.27  5333.4 2062.69  5379.9 2067.96  5455.2 2070.66  5766.3 2074.99
  5918.9 2079.52  6083.7 2081.28  6787.6 2081.80  7199.4 2087.73  7705.9 2091.77
#Mann=4,-1,0
  3236.6    0.05       0  4984.8    0.07       0  5012.9    0.05       0
  5267.8    0.05       0
#XS Ineff=2,0
       0                 5155.30    0.00 2070.40
Permanent Ineff=
       F       F
Bank Sta=4984.8,5012.9
Exp/Cntr=0.3,0.1

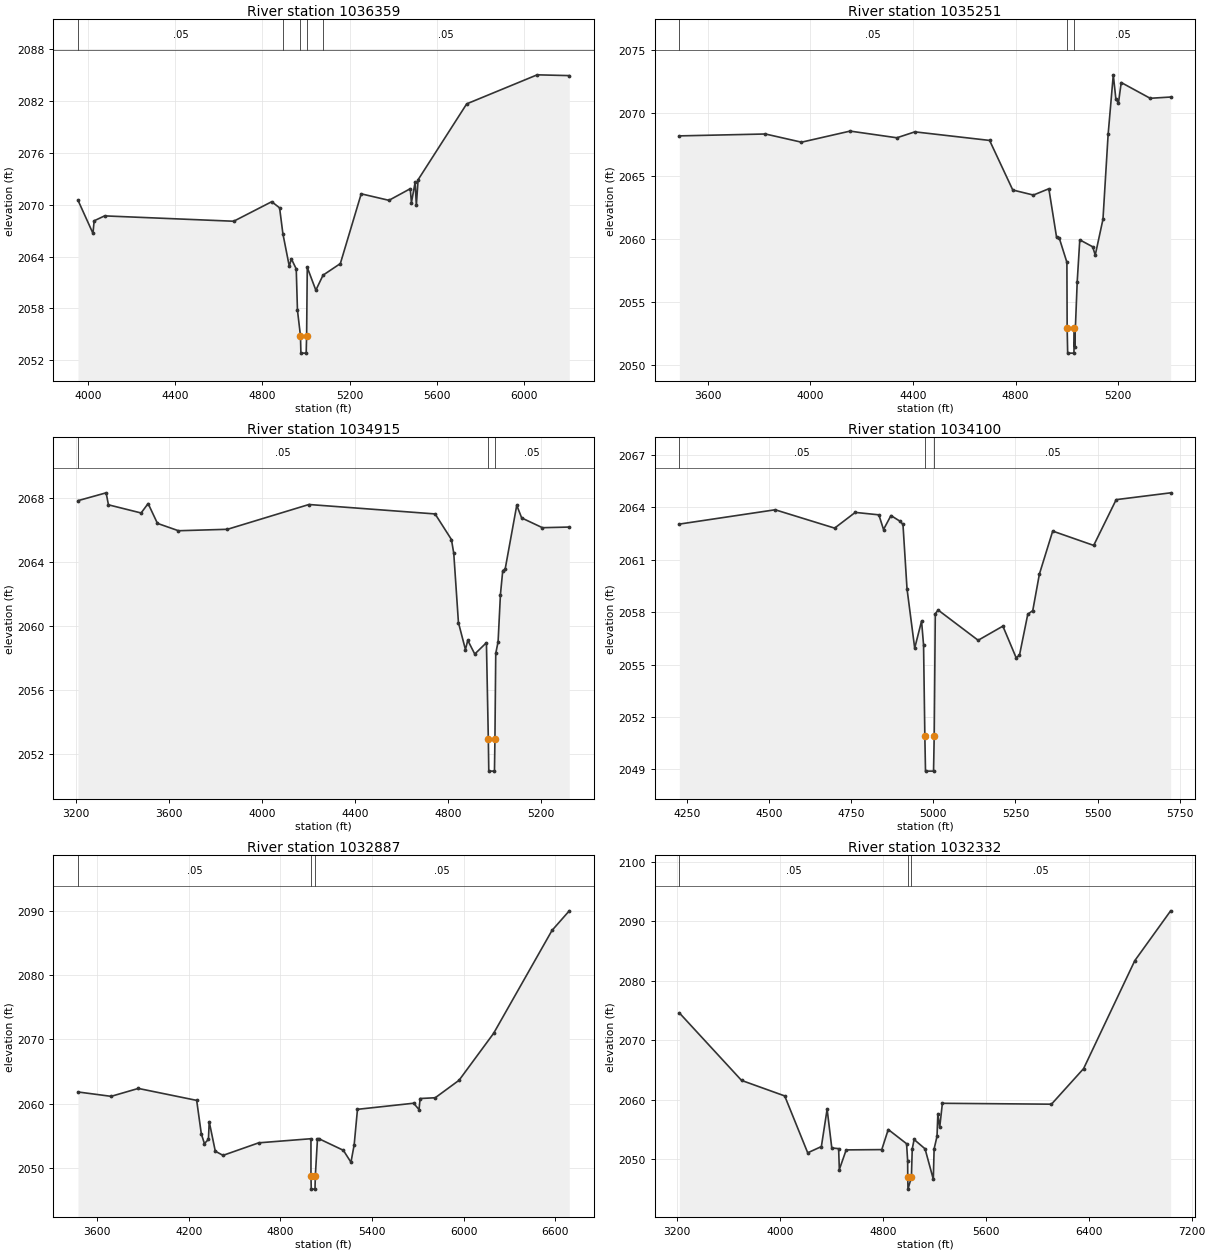
Type RM Length L Ch R = 1,1036359,1108,1108,1108
BEGIN DESCRIPTION:
Mapping XS 7fa8f23c
END DESCRIPTION:
XS GIS Cut Line= 3
      1319989.26      6955600.38      1320543.26      6955371.70
      1322027.15      6954642.77
#Sta/Elev= 30
  3954.9 2070.51  4023.6 2066.68  4029.0 2068.13  4076.9 2068.70  4668.9 2068.08
  4843.2 2070.34  4879.3 2069.63  4894.4 2066.64  4923.8 2062.86  4933.1 2063.74
  4955.6 2062.56  4961.2 2057.78  4975.0 2054.82  4977.0 2052.82  5001.2 2052.82
  5003.2 2054.82  5006.2 2062.74  5045.5 2060.10  5078.5 2061.84  5157.8 2063.18
  5253.5 2071.25  5380.6 2070.50  5478.3 2071.84  5483.8 2070.24  5500.8 2072.59
  5506.3 2069.92  5514.3 2072.88  5737.2 2081.66  6060.3 2085.02  6207.5 2084.93
#Mann=5,-1,0
  3954.9    0.05       0  4894.4    0.12       0  4975.0    0.07       0
  5003.2    0.12       0  5078.5    0.05       0
Bank Sta=4975,5003.2
Exp/Cntr=0.3,0.1

Type RM Length L Ch R = 1,1035251,336,336,336
BEGIN DESCRIPTION:
Mapping XS 8b60b616
END DESCRIPTION:
XS GIS Cut Line= 3
      1320300.86      6955536.56      1321372.79      6955627.32
      1322207.56      6955700.07
#Sta/Elev= 30
  3490.1 2068.20  3825.4 2068.35  3965.9 2067.70  4155.3 2068.58  4337.3 2068.05
  4407.5 2068.52  4698.6 2067.84  4788.9 2063.91  4869.2 2063.51  4929.4 2064.01
  4959.6 2060.15  4969.6 2060.12  4999.7 2058.18  5000.7 2052.98  5002.7 2050.98
  5027.1 2050.98  5029.1 2052.98  5029.8 2051.48  5039.9 2056.65  5049.9 2059.96
  5100.1 2059.41  5110.1 2058.75  5140.2 2061.59  5160.3 2068.32  5180.4 2073.04
  5190.4 2071.13  5200.5 2070.80  5211.3 2072.43  5324.1 2071.18  5403.8 2071.28
#Mann=3,-1,0
  3490.1    0.05       0  5000.7    0.03       0  5029.1    0.05       0
Bank Sta=5000.7,5029.1
Exp/Cntr=0.3,0.1

Type RM Length L Ch R = 1,1034915,815,815,815
BEGIN DESCRIPTION:
Mapping XS bcda02c0
END DESCRIPTION:
XS GIS Cut Line= 2
      1320064.42      6955845.98      1322170.11      6956009.10
#Sta/Elev= 30
  3209.6 2067.81  3330.5 2068.30  3340.6 2067.55  3481.0 2067.04  3511.1 2067.63
  3551.2 2066.39  3641.5 2065.93  3852.1 2066.02  4202.5 2067.57  4744.8 2066.98
  4815.0 2065.38  4825.0 2064.52  4845.1 2060.19  4875.2 2058.50  4885.2 2059.08
  4915.3 2058.22  4965.4 2058.93  4973.6 2052.90  4975.6 2050.90  5000.0 2050.90
  5002.0 2052.90  5005.5 2058.26  5015.6 2058.99  5025.6 2061.93  5035.6 2063.44
  5045.7 2063.51  5095.8 2067.52  5117.0 2066.73  5206.1 2066.12  5321.6 2066.16
#Mann=3,-1,0
  3209.6    0.05       0  4973.6    0.05       0  5002.0    0.05       0
Bank Sta=4973.6,5002
Exp/Cntr=0.3,0.1

Type RM Length L Ch R = 1,1034100,1213,1213,1213
BEGIN DESCRIPTION:
Clear Fork Brazos Rv 300.0
END DESCRIPTION:
XS GIS Cut Line= 3
      1321318.82      6957189.36      1322117.47      6956625.10
      1322195.59      6956112.99
#Sta/Elev= 30
  4226.8 2063.04  4518.6 2063.86  4699.6 2062.81  4762.4 2063.71  4834.3 2063.57
  4848.5 2062.73  4871.1 2063.53  4899.0 2063.20  4907.7 2063.02  4920.0 2059.34
  4943.4 2055.94  4964.3 2057.49  4970.4 2056.12  4974.3 2050.90  4976.3 2048.90
  5000.8 2048.90  5002.8 2050.90  5006.1 2057.91  5014.8 2058.12  5136.6 2056.39
  5211.9 2057.20  5252.3 2055.39  5262.4 2055.53  5287.7 2057.88  5302.9 2058.09
  5323.1 2060.18  5363.6 2062.64  5488.4 2061.82  5556.9 2064.44  5722.7 2064.83
#Mann=3,-1,0
  4226.8    0.05       0  4974.3    0.05       0  5002.8    0.05       0
Bank Sta=4974.3,5002.8
Exp/Cntr=0.3,0.1

Type RM Length L Ch R = 1,1032887,555,555,555
BEGIN DESCRIPTION:
Clear Fork Brazos Rv 299.0
END DESCRIPTION:
XS GIS Cut Line= 3
      1321409.55      6957601.21      1322905.00      6957338.00
      1324155.02      6956187.98
#Sta/Elev= 30
  3474.3 2061.81  3691.4 2061.13  3869.3 2062.36  4251.5 2060.50  4282.0 2055.28
  4302.3 2053.78  4328.5 2054.44  4333.6 2057.19  4373.4 2052.60  4424.1 2051.95
  4657.7 2053.90  4999.8 2054.54  4999.9 2048.70  5001.9 2046.70  5026.3 2046.70
  5028.3 2048.70  5042.4 2054.48  5049.2 2054.57  5211.9 2052.74  5261.8 2050.88
  5282.8 2053.60  5304.4 2059.11  5672.2 2060.06  5707.6 2059.06  5714.4 2060.79
  5813.6 2060.91  5969.6 2063.63  6195.9 2070.93  6578.1 2086.93  6691.3 2089.98
#Mann=3,-1,0
  3474.3    0.05       0  4999.9    0.03       0  5028.3    0.05       0
Bank Sta=4999.9,5028.3
Exp/Cntr=0.3,0.1

Type RM Length L Ch R = 1,1032332,819,819,819
BEGIN DESCRIPTION:
Clear Fork Brazos Rv 298.0
END DESCRIPTION:
XS GIS Cut Line= 3
      1321404.97      6958588.01      1323005.00      6957788.00
      1324255.01      6956187.99
#Sta/Elev= 30
  3216.8 2074.62  3700.4 2063.26  4035.8 2060.65  4214.7 2051.08  4320.9 2052.13
  4365.6 2058.42  4401.9 2051.90  4455.1 2051.78  4460.6 2048.27  4513.8 2051.57
  4790.5 2051.62  4840.8 2055.00  4983.3 2052.61  4991.7 2049.69  4992.3 2046.97
  4994.3 2044.97  5020.7 2046.97  5027.4 2051.75  5041.9 2053.32  5126.9 2051.75
  5191.1 2046.63  5197.4 2051.74  5220.0 2053.86  5226.4 2057.67  5240.8 2055.35
  5261.6 2059.41  6109.7 2059.26  6359.6 2065.25  6757.5 2083.41  7036.1 2091.79
#Mann=3,-1,0
  3216.8    0.05       0  4992.3    0.05       0  5020.7    0.05       0
Bank Sta=4992.3,5020.7
Exp/Cntr=0.3,0.1

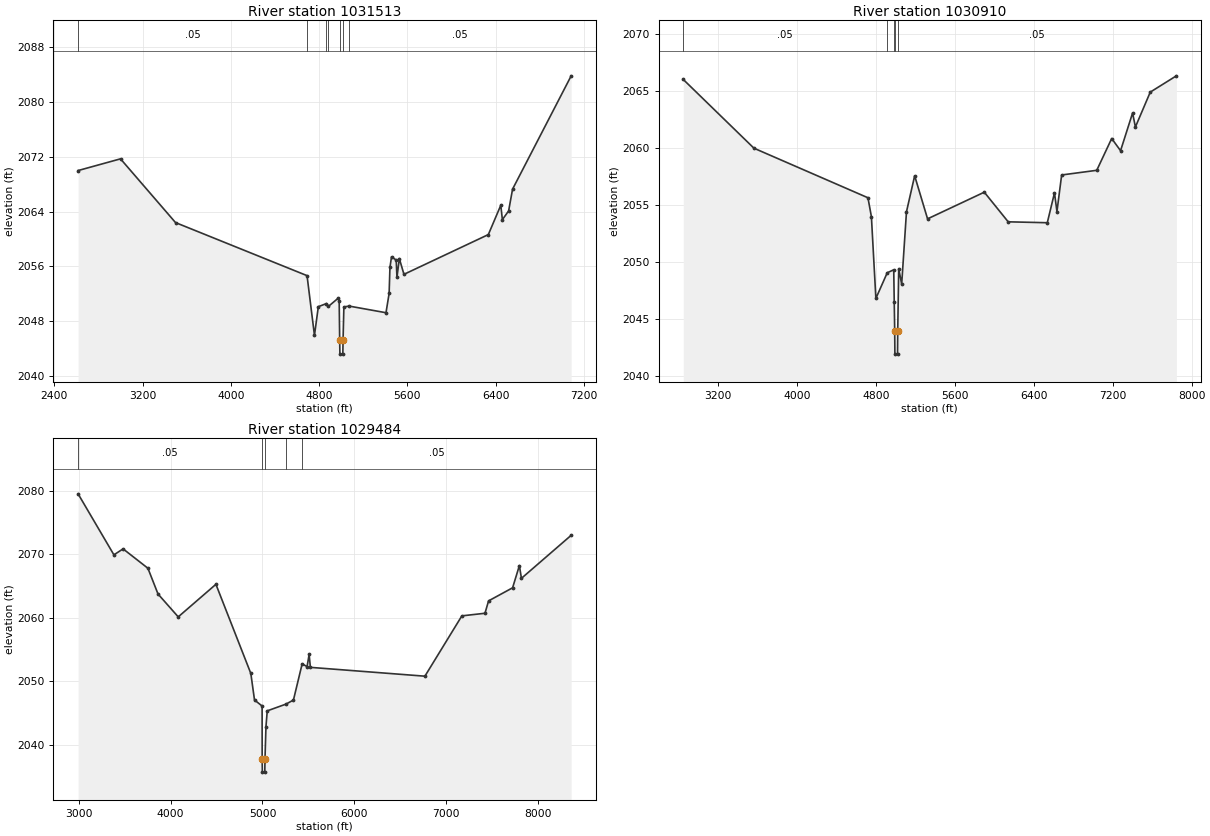
Type RM Length L Ch R = 1,1031513,603,603,603
BEGIN DESCRIPTION:
Clear Fork Brazos Rv 297.0
END DESCRIPTION:
XS GIS Cut Line= 3
      1321180.76      6958797.90      1323468.52      6958252.36
      1324893.97      6956686.12
#Sta/Elev= 30
  2614.6 2069.98  2999.3 2071.69  3498.0 2062.39  4690.1 2054.65  4757.3 2045.94
  4792.3 2050.12  4866.2 2050.58  4883.5 2050.16  4973.9 2051.38  4981.4 2050.93
  4985.9 2045.20  4987.9 2043.20  5014.5 2043.20  5016.5 2045.20  5023.9 2050.08
  5071.0 2050.21  5405.7 2049.24  5434.1 2052.06  5441.5 2055.84  5455.7 2057.40
  5498.3 2056.92  5505.0 2054.38  5526.6 2057.14  5568.5 2054.84  6333.4 2060.64
  6446.3 2064.92  6460.5 2062.82  6517.2 2064.09  6553.0 2067.27  7084.3 2083.80
#Mann=7,-1,0
  2614.6    0.05       0  4690.1    0.12       0  4866.2    0.05       0
  4883.5    0.12       0  4985.9    0.07       0  5016.5    0.12       0
  5071.0    0.05       0
Bank Sta=4985.9,5016.5
Exp/Cntr=0.3,0.1

Type RM Length L Ch R = 1,1030910,1426,1426,1426
BEGIN DESCRIPTION:
Clear Fork Brazos Rv 296.0
END DESCRIPTION:
XS GIS Cut Line= 3
      1321462.31      6958956.30      1323605.00      6958738.00
      1326425.02      6958357.96
#Sta/Elev= 30
  2846.2 2065.99  3562.6 2059.96  4718.5 2055.61  4753.5 2053.95  4798.9 2046.78
  4914.1 2049.03  4979.9 2049.29  4985.0 2046.48  4989.7 2043.89  4991.7 2041.89
  5018.4 2041.89  5020.4 2043.89  5030.3 2049.39  5060.5 2048.03  5109.1 2054.38
  5192.0 2057.54  5322.9 2053.76  5898.0 2056.10  6140.2 2053.50  6536.8 2053.42
  6609.6 2056.04  6634.6 2054.40  6682.3 2057.61  7038.2 2058.02  7189.6 2060.81
  7279.5 2059.74  7401.5 2063.05  7430.0 2061.82  7580.6 2064.88  7845.5 2066.31
#Mann=5,-1,0
  2846.2    0.05       0  4914.1    0.12       0  4985.0    0.05       0
  4989.7    0.05       0  5020.4    0.05       0
Bank Sta=4989.7,5020.4
Exp/Cntr=0.3,0.1

Type RM Length L Ch R = 1,1029484,1397,1397,1397
BEGIN DESCRIPTION:
Clear Fork Brazos Rv 295.0
END DESCRIPTION:
XS GIS Cut Line= 3
      1321855.04      6959988.00      1323855.00      6959988.00
      1326865.03      6958481.13
#Sta/Elev= 30
  2993.4 2079.55  3383.4 2069.94  3483.4 2070.88  3753.4 2067.83  3863.4 2063.77
  4083.4 2060.17  4493.4 2065.30  4873.4 2051.26  4913.4 2047.08  4996.2 2046.13
  4996.7 2037.72  4998.7 2035.72  5025.4 2035.72  5027.4 2037.72  5038.1 2042.90
  5052.0 2045.37  5255.6 2046.43  5337.0 2047.07  5432.0 2052.78  5485.4 2052.33
  5507.8 2054.25  5521.4 2052.22  6767.6 2050.83  7169.9 2060.33  7421.4 2060.74
  7460.5 2062.69  7722.0 2064.75  7795.8 2068.25  7818.1 2066.24  8359.5 2073.02
#Mann=5,-1,0
  2993.4    0.05       0  4996.7    0.05       0  5027.4    0.05       0
  5255.6    0.12       0  5432.0    0.05       0
Bank Sta=4996.7,5027.4
Exp/Cntr=0.3,0.1