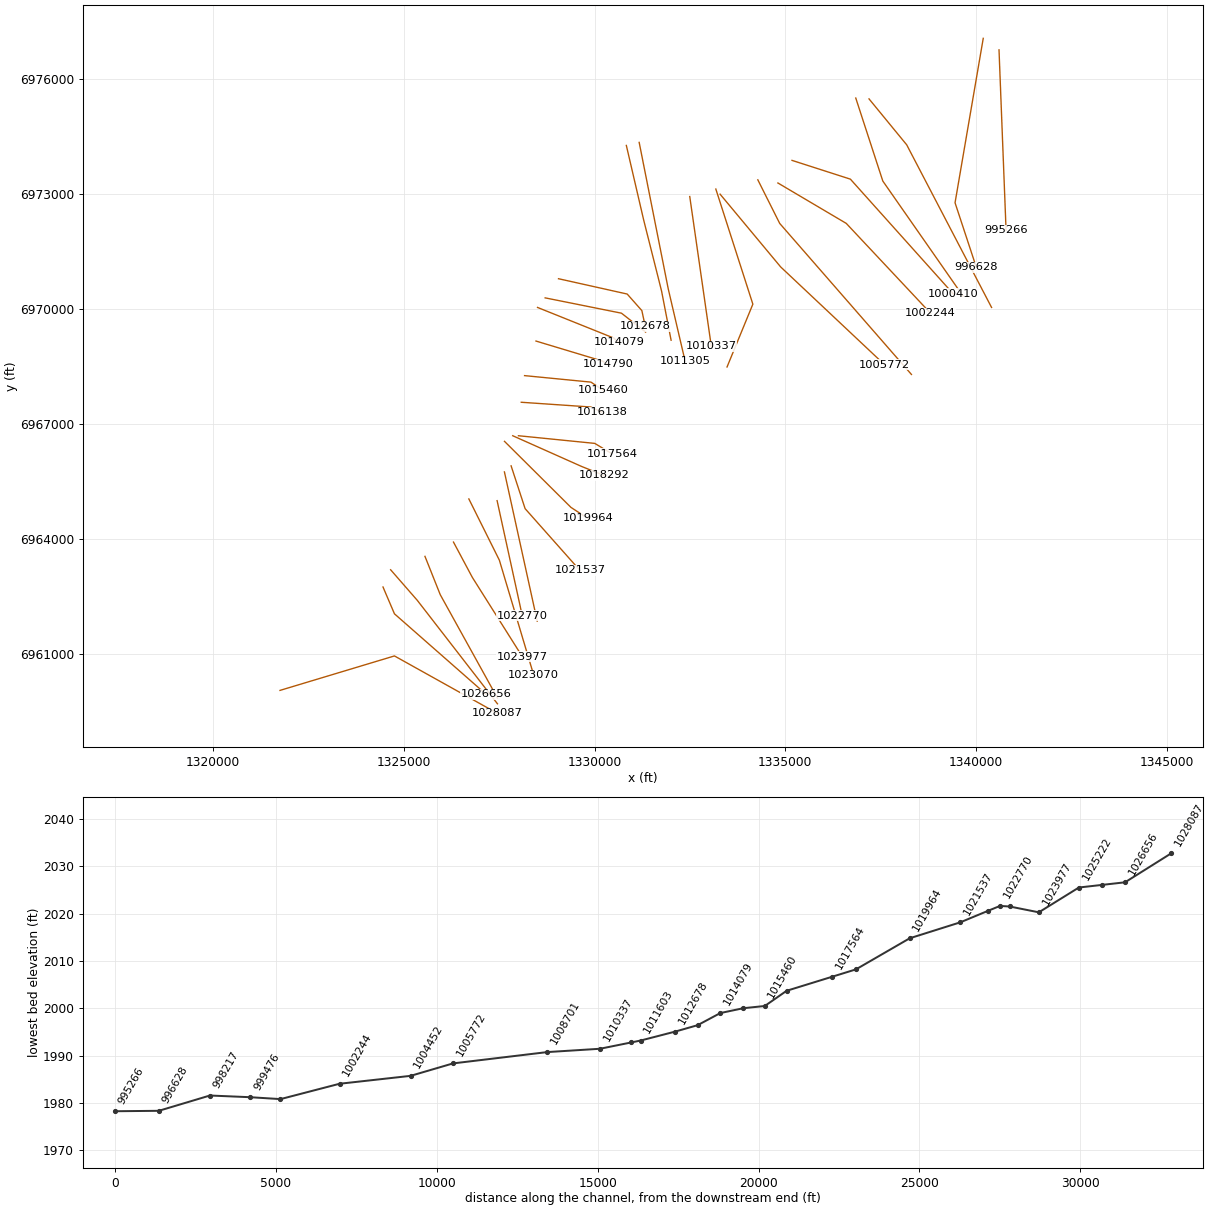
HEC-RAS study Clear Fork Brazos Rv.prj: Clear Fork Brazos Rv Base Level Engineering

--- Clear Fork Brazos Rv.g01 (geometry) --- (continued)

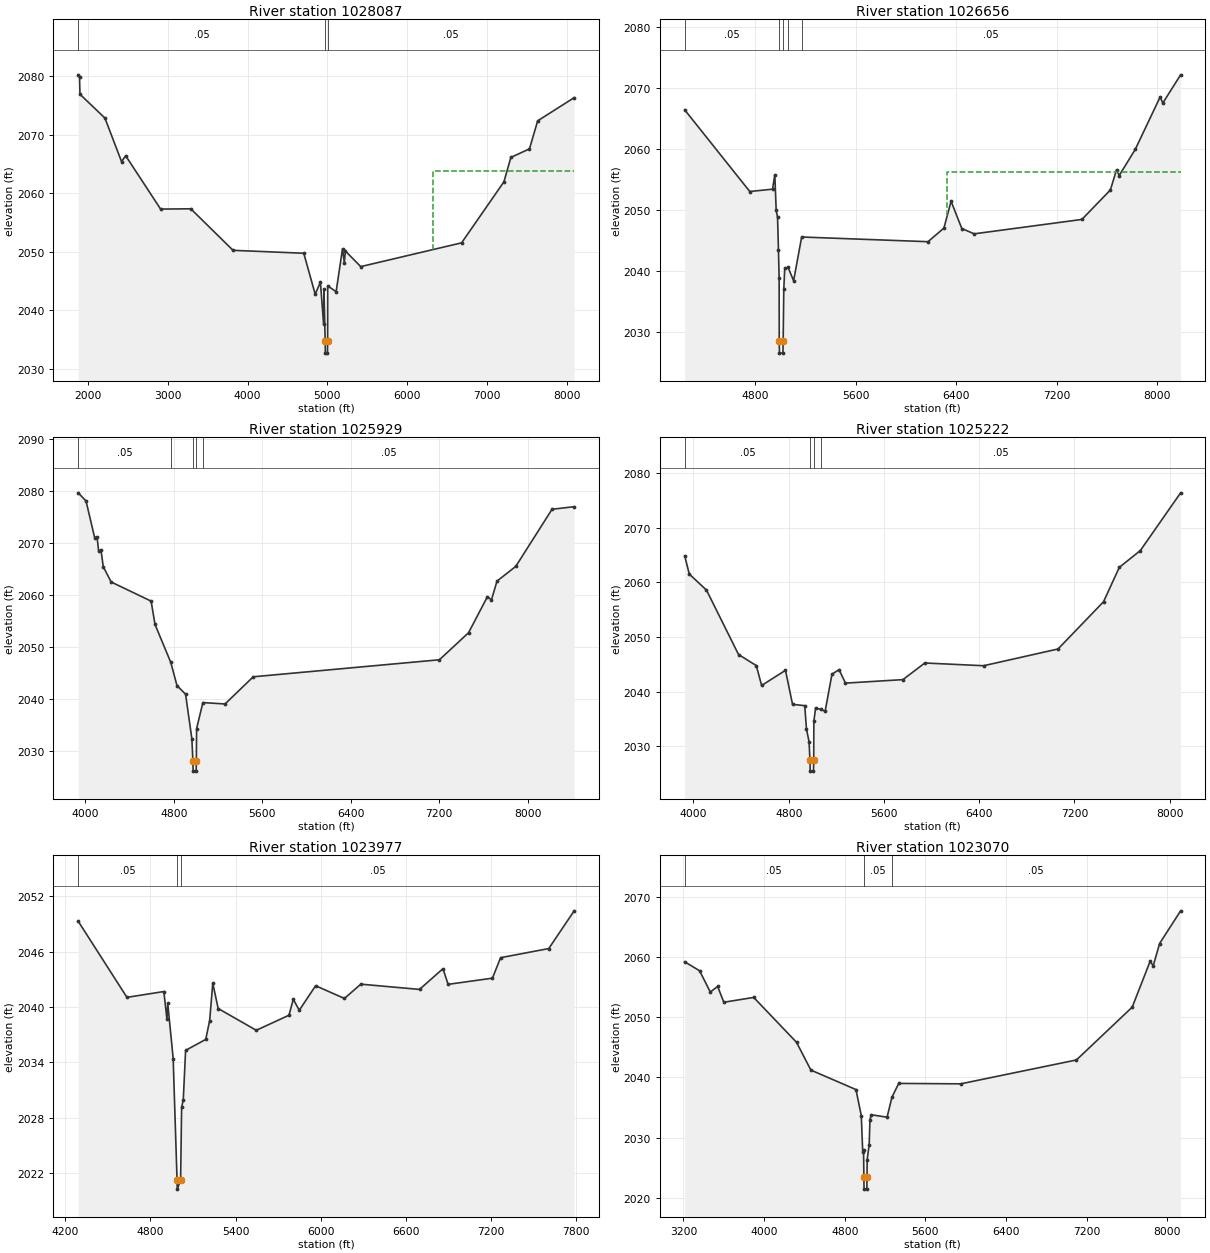
Type RM Length L Ch R = 1,1028087,1431,1431,1431
BEGIN DESCRIPTION:
Clear Fork Brazos Rv 294.0
END DESCRIPTION:
XS GIS Cut Line= 3
      1321755.04      6960038.01      1324755.00      6960938.00
      1327454.97      6959438.02
#Sta/Elev= 30
  1874.3 2080.20  1890.8 2079.81  1896.0 2076.89  2209.2 2072.82  2418.0 2065.38
  2469.4 2066.39  2907.8 2057.28  3286.3 2057.33  3816.2 2050.24  4703.6 2049.74
  4847.1 2042.74  4912.4 2044.82  4951.5 2037.73  4956.8 2043.56  4972.1 2034.69
  4974.1 2032.69  5000.9 2032.69  5002.9 2034.69  5003.7 2044.18  5109.3 2043.17
  5189.4 2050.51  5212.3 2048.16  5226.0 2050.11  5418.2 2047.46  6683.4 2051.52
  7214.2 2061.94  7301.1 2066.10  7534.5 2067.56  7637.5 2072.35  8095.0 2076.30
#Mann=3,-1,0
  1874.3    0.05       0  4972.1    0.05       0  5002.9    0.05       0
#XS Ineff=2,0
       0                 6325.30    0.00 2063.73
Permanent Ineff=
       F       F
Bank Sta=4972.1,5002.9
Exp/Cntr=0.3,0.1

Type RM Length L Ch R = 1,1026656,727,727,727
BEGIN DESCRIPTION:
Clear Fork Brazos Rv 293.0
END DESCRIPTION:
XS GIS Cut Line= 3
      1324455.02      6962737.96      1324755.00      6962038.00
      1327155.02      6959937.98
#Sta/Elev= 30
  4237.6 2066.48  4756.1 2053.09  4937.5 2053.47  4955.6 2055.85  4966.5 2050.04
  4977.4 2048.84  4984.6 2043.57  4990.1 2038.89  4990.8 2028.59  4992.8 2026.59
  5020.1 2026.59  5022.1 2028.59  5027.1 2037.09  5034.7 2040.47  5061.2 2040.64
  5105.4 2038.46  5169.5 2045.63  6175.6 2044.86  6302.7 2047.09  6359.7 2051.49
  6445.1 2047.02  6543.8 2046.15  7401.8 2048.51  7628.7 2053.34  7678.0 2056.67
  7698.9 2055.71  7827.0 2060.00  8025.4 2068.60  8046.3 2067.59  8188.2 2072.22
#Mann=5,-1,0
  4237.6    0.05       0  4990.8    0.05       0  5022.1    0.05       0
  5061.2    0.12       0  5169.5    0.05       0
#XS Ineff=2,0
       0                 6328.70    0.00 2056.25
Permanent Ineff=
       F       F
Bank Sta=4990.8,5022.1
Exp/Cntr=0.3,0.1

Type RM Length L Ch R = 1,1025929,707,707,707
BEGIN DESCRIPTION:
Clear Fork Brazos Rv 292.0
END DESCRIPTION:
XS GIS Cut Line= 3
      1324654.98      6963188.02      1325355.00      6962388.00
      1327455.02      6959687.97
#Sta/Elev= 30
  3936.8 2079.66  4007.5 2078.08  4085.4 2071.03  4107.2 2071.19  4121.4 2068.42
  4142.3 2068.69  4163.2 2065.43  4234.4 2062.48  4596.0 2058.79  4631.1 2054.30
  4773.7 2046.98  4829.5 2042.52  4907.3 2040.85  4964.2 2032.29  4973.6 2028.03
  4975.6 2026.03  5002.9 2026.03  5004.9 2028.03  5007.1 2034.22  5063.9 2039.24
  5264.1 2038.97  5519.3 2044.21  7202.4 2047.49  7465.7 2052.70  7635.8 2059.62
  7672.9 2059.04  7722.7 2062.64  7892.8 2065.49  8220.4 2076.49  8420.4 2076.99
#Mann=5,-1,0
  3936.8    0.05       0  4773.7     0.1       0  4973.6    0.07       0
  5004.9     0.1       0  5063.9    0.05       0
Bank Sta=4973.6,5004.9
Exp/Cntr=0.3,0.1

Type RM Length L Ch R = 1,1025222,1245,1245,1245
BEGIN DESCRIPTION:
Clear Fork Brazos Rv 291.0
END DESCRIPTION:
XS GIS Cut Line= 3
      1325555.01      6963537.98      1325955.00      6962538.00
      1327455.00      6959838.00
#Sta/Elev= 30
  3926.1 2064.85  3965.1 2061.51  4109.2 2058.59  4378.4 2046.81  4527.9 2044.78
  4572.3 2041.15  4772.9 2043.92  4832.1 2037.70  4934.5 2037.46  4949.3 2033.17
  4970.8 2030.88  4978.5 2027.49  4980.5 2025.49  5007.9 2025.49  5009.9 2027.49
  5011.1 2034.58  5026.0 2037.07  5067.0 2036.76  5106.1 2036.46  5163.3 2043.21
  5222.8 2044.05  5276.5 2041.58  5759.3 2042.22  5943.4 2045.26  6436.5 2044.76
  7062.2 2047.82  7444.3 2056.46  7577.0 2062.75  7753.2 2065.81  8091.8 2076.37
#Mann=4,-1,0
  3926.1    0.05       0  4978.5    0.07       0  5009.9    0.05       0
  5067.0    0.05       0
Bank Sta=4978.5,5009.9
Exp/Cntr=0.3,0.1

Type RM Length L Ch R = 1,1023977,907,907,907
BEGIN DESCRIPTION:
Mapping XS 7f781855
END DESCRIPTION:
XS GIS Cut Line= 3
      1326302.07      6963911.09      1326796.51      6962988.76
      1328108.65      6960915.96
#Sta/Elev= 30
  4290.0 2049.29  4633.9 2041.04  4894.3 2041.67  4916.2 2038.65  4921.9 2040.38
  4960.1 2034.41  4987.5 2021.25  4989.1 2020.25  5012.6 2021.25  5019.7 2029.10
  5031.5 2029.96  5047.8 2035.29  5189.9 2036.48  5217.6 2038.53  5239.5 2042.57
  5277.7 2039.83  5546.6 2037.47  5777.1 2039.10  5807.7 2040.83  5850.0 2039.64
  5965.3 2042.30  6168.7 2040.92  6284.2 2042.47  6698.5 2041.90  6864.1 2044.15
  6900.2 2042.45  7213.0 2043.12  7270.6 2045.34  7610.5 2046.33  7789.7 2050.42
#Mann=3,-1,0
  4290.0    0.05       0  4987.5    0.05       0  5012.6    0.05       0
Bank Sta=4987.5,5012.6
Exp/Cntr=0.3,0.1

Type RM Length L Ch R = 1,1023070,300,300,300
BEGIN DESCRIPTION:
Clear Fork Brazos Rv 288.0
END DESCRIPTION:
XS GIS Cut Line= 3
      1326705.02      6965037.96      1327505.00      6963438.00
      1328405.00      6960438.00
#Sta/Elev= 30
  3211.9 2059.18  3360.0 2057.69  3466.2 2054.16  3538.9 2055.09  3600.4 2052.47
  3896.7 2053.27  4321.5 2045.83  4464.1 2041.22  4911.3 2037.99  4964.4 2033.67
  4978.4 2027.67  4986.7 2028.04  4989.9 2023.48  4991.9 2021.48  5019.3 2021.48
  5021.3 2023.48  5022.5 2026.35  5042.5 2028.87  5050.3 2032.99  5063.4 2033.81
  5220.0 2033.41  5268.7 2036.73  5335.7 2039.01  5950.8 2038.94  7099.2 2042.90
  7652.6 2051.66  7830.0 2059.25  7861.4 2058.53  7924.0 2062.20  8132.8 2067.63
#Mann=3,-1,0
  3211.9    0.05       0  4989.9    0.05       0  5268.7    0.05       0
Bank Sta=4989.9,5021.3
Exp/Cntr=0.3,0.1

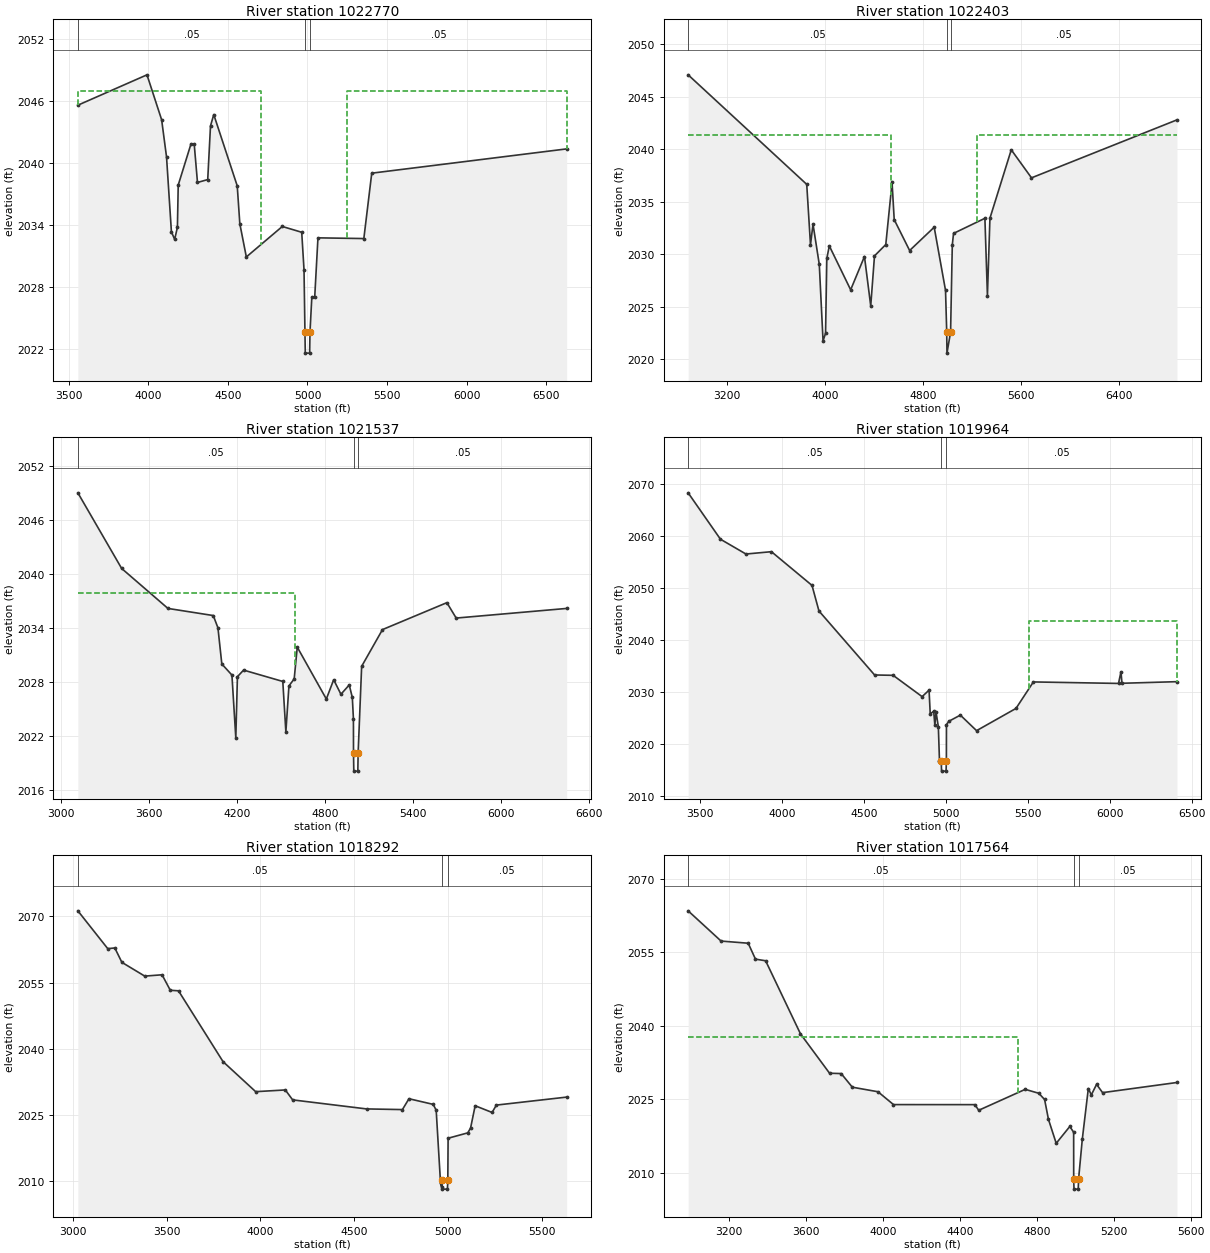
Type RM Length L Ch R = 1,1022770,367,367,367
BEGIN DESCRIPTION:
Mapping XS 18e8909a
END DESCRIPTION:
XS GIS Cut Line= 2
      1327445.48      6964992.40      1328104.05      6961991.31
#Sta/Elev= 30
  3556.8 2045.60  3991.3 2048.54  4083.4 2044.19  4114.2 2040.59  4144.9 2033.34
  4165.3 2032.61  4182.6 2033.78  4187.7 2037.87  4267.7 2041.84  4288.2 2041.83
  4308.7 2038.12  4373.1 2038.40  4390.6 2043.60  4411.1 2044.69  4558.6 2037.79
  4574.9 2034.12  4615.8 2030.91  4841.9 2033.86  4963.9 2033.30  4978.4 2029.66
  4984.3 2023.60  4986.3 2021.60  5013.8 2021.60  5015.8 2023.60  5027.3 2026.99
  5045.8 2027.07  5066.0 2032.76  5354.4 2032.69  5404.1 2039.02  6629.3 2041.37
#Mann=3,-1,0
  3556.8    0.05       0  4984.3    0.05       0  5015.8    0.05       0
#XS Ineff=2,0
    0.00 4708.00 2046.98 5250.00    0.00 2046.98
Permanent Ineff=
       F       F
Bank Sta=4984.3,5015.8
Exp/Cntr=0.3,0.1

Type RM Length L Ch R = 1,1022403,866,866,866
BEGIN DESCRIPTION:
Mapping XS c065a330
END DESCRIPTION:
XS GIS Cut Line= 2
      1327637.32      6965743.18      1328496.49      6961847.70
#Sta/Elev= 30
  2884.0 2047.08  3851.9 2036.65  3882.6 2030.90  3903.1 2032.86  3954.3 2029.03
  3985.0 2021.75  4005.5 2022.47  4015.8 2029.60  4036.2 2030.79  4210.3 2026.61
  4323.0 2029.78  4374.2 2025.08  4404.9 2029.84  4497.0 2030.92  4548.2 2036.83
  4565.8 2033.29  4691.6 2030.35  4892.1 2032.57  4984.6 2026.55  4994.3 2022.58
  4996.3 2020.58  5025.8 2022.58  5039.8 2030.88  5050.0 2031.98  5305.9 2033.42
  5326.5 2026.06  5347.0 2033.43  5521.1 2039.94  5686.1 2037.27  6873.1 2042.79
#Mann=3,-1,0
  2884.0    0.05       0  4994.3    0.05       0  5025.8    0.05       0
#XS Ineff=2,0
    0.00 4537.60 2041.36 5244.00    0.00 2041.36
Permanent Ineff=
       F       F
Bank Sta=4994.3,5025.8
Exp/Cntr=0.3,0.1

Type RM Length L Ch R = 1,1021537,1573,1573,1573
BEGIN DESCRIPTION:
Mapping XS 74eb371e
END DESCRIPTION:
XS GIS Cut Line= 3
      1327812.48      6965901.67      1328179.51      6964783.89
      1329614.21      6963174.02
#Sta/Elev= 30
  3114.8 2049.05  3413.4 2040.65  3729.1 2036.21  4038.0 2035.42  4069.9 2034.06
  4096.4 2030.04  4165.3 2028.81  4191.8 2021.83  4202.8 2028.63  4244.9 2029.36
  4512.2 2028.10  4533.1 2022.49  4554.0 2027.60  4589.9 2028.39  4610.8 2031.91
  4809.0 2026.15  4859.1 2028.29  4908.5 2026.68  4965.3 2027.71  4986.2 2026.32
  4993.7 2023.96  4994.3 2020.14  4996.3 2018.14  5023.8 2018.14  5025.8 2020.14
  5049.8 2029.78  5191.9 2033.86  5630.9 2036.85  5694.4 2035.14  6447.7 2036.21
#Mann=3,-1,0
  3114.8    0.05       0  4994.3    0.03       0  5025.8    0.05       0
#XS Ineff=2,0
    0.00 4597.40 2037.87               0
Permanent Ineff=
       F       F
Bank Sta=4994.3,5025.8
Exp/Cntr=0.3,0.1

Type RM Length L Ch R = 1,1019964,1672,1672,1672
BEGIN DESCRIPTION:
Clear Fork Brazos Rv 285.0
END DESCRIPTION:
XS GIS Cut Line= 3
      1327639.35      6966541.21      1329381.59      6964816.57
      1329826.93      6964527.54
#Sta/Elev= 30
  3427.9 2068.34  3625.1 2059.41  3780.7 2056.56  3936.2 2057.01  4183.7 2050.52
  4226.1 2045.60  4565.5 2033.28  4678.7 2033.21  4855.5 2029.11  4897.9 2030.36
  4905.0 2025.79  4926.2 2026.29  4933.3 2023.60  4940.4 2026.15  4954.5 2023.33
  4961.5 2016.74  4972.1 2016.77  4974.1 2014.77  5001.6 2014.77  5003.6 2016.77
  5004.0 2023.69  5018.1 2024.36  5088.8 2025.55  5187.8 2022.56  5428.2 2026.84
  5534.3 2031.94  6053.8 2031.65  6068.9 2033.90  6074.9 2031.68  6410.3 2031.99
#Mann=3,-1,0
  3427.9    0.05       0  4972.1    0.05       0  5003.6    0.05       0
#XS Ineff=2,0
       0                 5505.30    0.00 2043.76
Permanent Ineff=
       F       F
Bank Sta=4972.1,5003.6
Exp/Cntr=0.3,0.1

Type RM Length L Ch R = 1,1018292,728,728,728
BEGIN DESCRIPTION:
Clear Fork Brazos Rv 284.0
END DESCRIPTION:
XS GIS Cut Line= 3
      1327855.04      6966687.98      1329655.00      6965888.00
      1330243.91      6965652.44
#Sta/Elev= 30
  3027.5 2071.25  3186.8 2062.68  3224.4 2062.84  3262.0 2059.58  3383.8 2056.46
  3476.1 2056.76  3519.9 2053.25  3563.7 2053.13  3801.0 2037.08  3974.7 2030.28
  4132.7 2030.67  4171.7 2028.42  4565.7 2026.37  4756.5 2026.22  4791.4 2028.68
  4920.6 2027.40  4936.4 2026.07  4959.6 2009.55  4965.1 2008.70  4966.8 2010.20
  4968.8 2008.20  4996.3 2008.20  4998.3 2010.20  4999.9 2019.73  5104.9 2020.95
  5119.7 2022.06  5144.0 2027.09  5234.2 2025.57  5257.1 2027.24  5631.5 2029.05
#Mann=3,-1,0
  3027.5    0.05       0  4966.8    0.05       0  4998.3    0.05       0
Bank Sta=4966.8,4998.3
Exp/Cntr=0.3,0.1

Type RM Length L Ch R = 1,1017564,1426,1426,1426
BEGIN DESCRIPTION:
Clear Fork Brazos Rv 283.0
END DESCRIPTION:
XS GIS Cut Line= 3
      1328004.95      6966688.00      1330005.00      6966488.00
      1330455.85      6966217.49
#Sta/Elev= 30
  2990.5 2063.46  3161.4 2057.29  3302.1 2056.85  3339.8 2053.60  3392.5 2053.27
  3573.4 2038.35  3724.2 2030.32  3784.5 2030.25  3842.3 2027.47  3975.4 2026.54
  4055.8 2023.92  4477.9 2023.91  4498.0 2022.76  4739.2 2027.03  4809.6 2026.23
  4839.7 2024.96  4859.8 2020.90  4900.0 2016.02  4970.4 2019.45  4990.5 2018.28
  4990.7 2008.67  4992.3 2006.67  5014.3 2006.67  5015.9 2008.67  5035.5 2016.93
  5066.6 2027.20  5082.2 2025.90  5109.4 2028.05  5140.5 2026.36  5526.3 2028.43
#Mann=3,-1,0
  2990.5    0.05       0  4990.7    0.05       0  5015.9    0.05       0
#XS Ineff=2,0
    0.00 4700.00 2037.62               0
Permanent Ineff=
       F       F
Bank Sta=4990.7,5015.9
Exp/Cntr=0.3,0.1

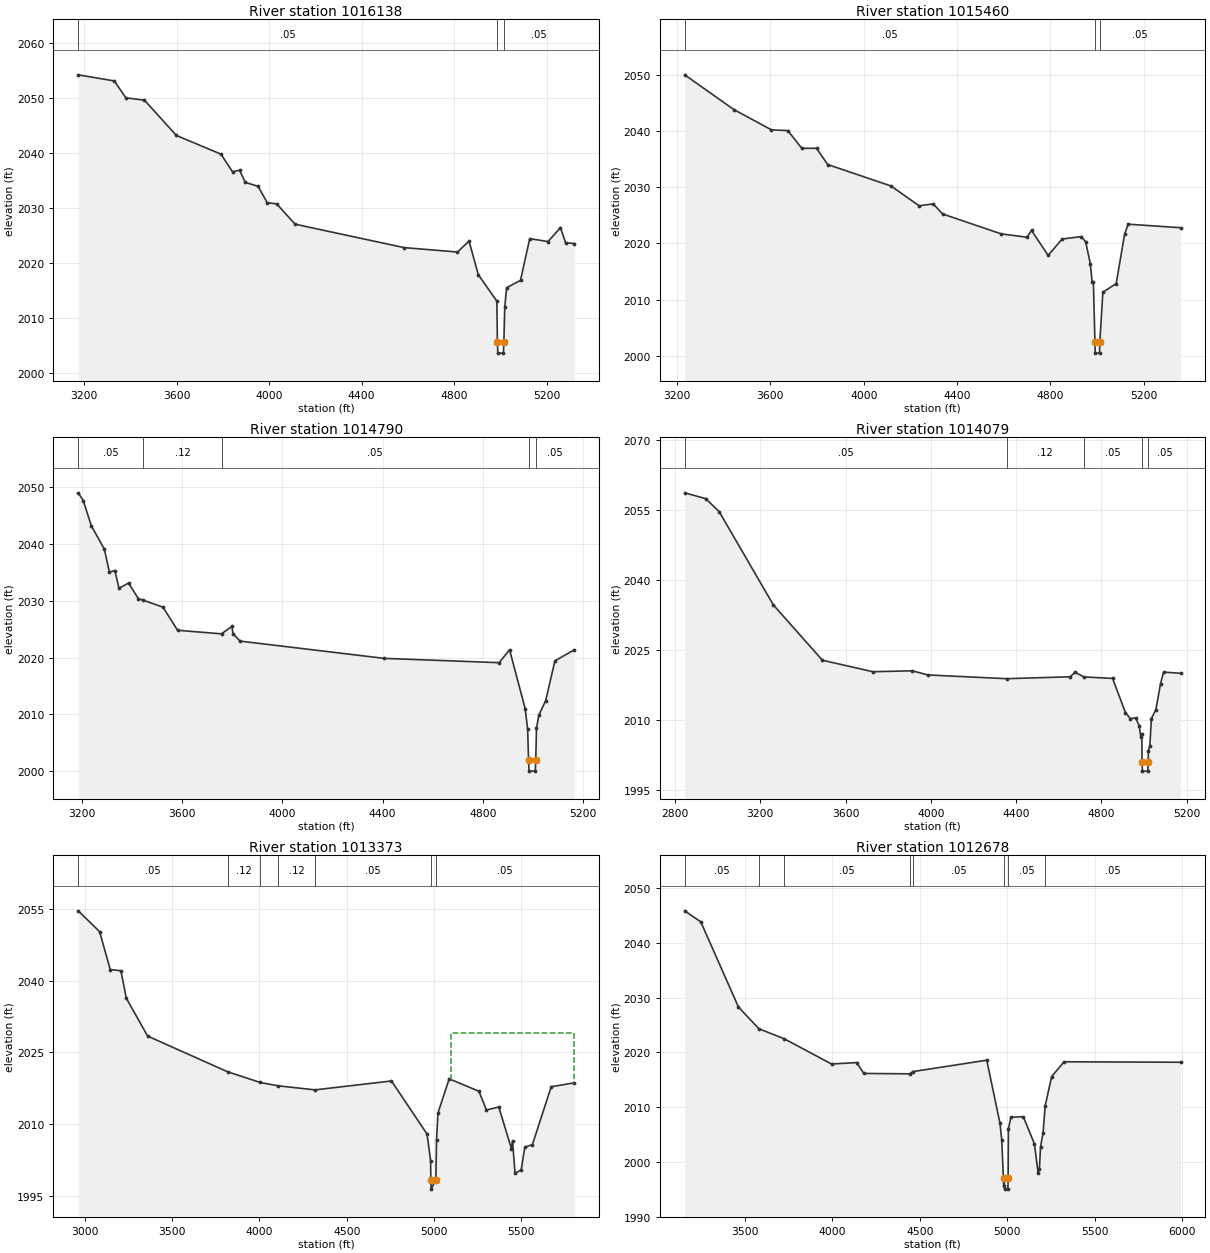
Type RM Length L Ch R = 1,1016138,678,678,678
BEGIN DESCRIPTION:
Clear Fork Brazos Rv 282.0
END DESCRIPTION:
XS GIS Cut Line= 3
      1328079.34      6967561.92      1329905.00      6967438.00
      1330188.37      6967302.63
#Sta/Elev= 30
  3174.9 2054.19  3330.9 2053.08  3381.0 2050.02  3461.2 2049.59  3599.2 2043.19
  3792.0 2039.79  3842.1 2036.59  3872.2 2036.88  3897.3 2034.68  3952.3 2033.95
  3992.4 2030.97  4032.5 2030.78  4112.7 2027.08  4583.8 2022.83  4814.3 2022.03
  4864.4 2024.02  4904.5 2017.91  4984.7 2013.11  4987.0 2005.68  4988.7 2003.68
  5013.1 2003.68  5014.9 2005.68  5018.9 2012.11  5026.9 2015.55  5086.9 2016.88
  5126.7 2024.46  5205.9 2023.93  5259.7 2026.45  5281.8 2023.72  5318.8 2023.57
#Mann=3,-1,0
  3174.9    0.05       0  4987.0    0.05       0  5014.9    0.05       0
Bank Sta=4987,5014.9
Exp/Cntr=0.3,0.1

Type RM Length L Ch R = 1,1015460,670,670,670
BEGIN DESCRIPTION:
Clear Fork Brazos Rv 281.0
END DESCRIPTION:
XS GIS Cut Line= 3
      1328165.33      6968257.53      1329905.00      6968088.00
      1330218.87      6967879.73
#Sta/Elev= 30
  3233.0 2050.00  3443.7 2043.82  3604.4 2040.21  3674.8 2040.07  3735.0 2036.92
  3797.8 2036.93  3845.6 2034.04  4116.8 2030.22  4237.4 2026.69  4297.7 2027.03
  4337.9 2025.24  4589.1 2021.69  4699.6 2021.10  4718.9 2022.31  4790.0 2017.87
  4850.3 2020.78  4932.5 2021.21  4950.8 2020.28  4970.9 2016.36  4978.4 2013.15
  4983.9 2013.15  4990.6 2002.47  4991.9 2000.47  5010.2 2000.47  5011.5 2002.47
  5024.5 2011.30  5081.7 2012.86  5117.7 2021.65  5132.8 2023.42  5357.6 2022.79
#Mann=3,-1,0
  3233.0    0.05       0  4990.6    0.05       0  5011.5    0.05       0
Bank Sta=4990.6,5011.5
Exp/Cntr=0.3,0.1

Type RM Length L Ch R = 1,1014790,711,711,711
BEGIN DESCRIPTION:
Clear Fork Brazos Rv 280.0
END DESCRIPTION:
XS GIS Cut Line= 3
      1328464.86      6969160.06      1330205.00      6968638.00
      1330344.80      6968552.39
#Sta/Elev= 30
  3184.4 2049.04  3204.6 2047.68  3236.8 2043.23  3289.0 2039.10  3309.0 2035.06
  3330.7 2035.34  3347.3 2032.22  3385.5 2033.14  3424.7 2030.38  3445.0 2030.11
  3523.0 2028.89  3581.3 2024.82  3756.7 2024.19  3797.9 2025.50  3803.2 2024.18
  3831.0 2022.91  4406.1 2019.87  4865.4 2019.11  4907.2 2021.38  4969.8 2010.95
  4979.4 2007.34  4983.0 2002.00  4985.0 2000.00  5009.9 2000.00  5011.8 2002.00
  5014.7 2007.58  5024.3 2009.89  5051.5 2012.43  5088.2 2019.42  5165.1 2021.37
#Mann=5,-1,0
  3184.4    0.05       0  3445.0    0.12       0  3756.7    0.05       0
  4983.0    0.05       0  5011.8    0.05       0
Bank Sta=4983,5011.8
Exp/Cntr=0.3,0.1

Type RM Length L Ch R = 1,1014079,706,706,706
BEGIN DESCRIPTION:
Clear Fork Brazos Rv 279.0
END DESCRIPTION:
XS GIS Cut Line= 3
      1328504.98      6970038.01      1330505.00      6969238.00
      1330633.15      6969122.66
#Sta/Elev= 30
  2845.3 2058.59  2943.6 2057.35  3006.9 2054.58  3261.3 2034.58  3491.5 2022.73
  3728.5 2020.27  3912.9 2020.47  3985.6 2019.58  4355.5 2018.78  4654.7 2019.19
  4676.3 2020.16  4718.2 2019.16  4852.6 2018.84  4913.2 2011.49  4936.1 2010.24
  4960.3 2010.36  4977.8 2008.71  4984.6 2006.38  4990.0 2006.95  4990.9 2000.98
  4992.8 1998.98  5017.8 1998.98  5019.7 2000.98  5020.7 2003.38  5027.4 2004.44
  5034.9 2010.25  5055.8 2012.17  5077.5 2017.68  5091.7 2020.20  5171.8 2019.93
#Mann=5,-1,0
  2845.3    0.05       0  4355.5    0.12       0  4718.2    0.05       0
  4990.9    0.05       0  5019.7    0.05       0
Bank Sta=4990.9,5019.7
Exp/Cntr=0.3,0.1

Type RM Length L Ch R = 1,1013373,695,695,695
BEGIN DESCRIPTION:
Clear Fork Brazos Rv 278.0
END DESCRIPTION:
XS GIS Cut Line= 3
      1328704.98      6970288.00      1330705.00      6969888.00
      1331338.04      6969395.64
#Sta/Elev= 30
  2961.6 2054.57  3084.0 2050.23  3145.2 2042.30  3206.4 2042.05  3237.0 2036.33
  3359.3 2028.40  3817.1 2020.95  4004.1 2018.71  4105.7 2018.01  4318.7 2017.16
  4756.5 2019.02  4960.4 2007.92  4980.8 2002.37  4982.0 1998.42  4983.9 1996.42
  5010.8 1998.42  5014.8 2006.72  5022.9 2012.34  5087.2 2019.46  5257.3 2016.88
  5300.7 2012.96  5371.3 2013.58  5443.7 2004.90  5450.1 2006.51  5464.5 1999.72
  5499.8 2000.44  5520.6 2005.18  5564.1 2005.74  5671.8 2017.81  5803.2 2018.63
#Mann=7,-1,0
  2961.6    0.05       0  3817.1    0.12       0  4004.1    0.05       0
  4105.7    0.12       0  4318.7    0.05       0  4982.0    0.05       0
  5010.8    0.05       0
#XS Ineff=2,0
       0                 5097.70    0.00 2028.98
Permanent Ineff=
       F       F
Bank Sta=4982,5010.8
Exp/Cntr=0.3,0.1

Type RM Length L Ch R = 1,1012678,1075,1075,1075
BEGIN DESCRIPTION:
Clear Fork Brazos Rv 277.0
END DESCRIPTION:
XS GIS Cut Line= 4
      1329055.03      6970787.99      1330855.00      6970388.00
      1331239.59      6969955.33      1331326.45      6969551.43
#Sta/Elev= 30
  3155.1 2045.83  3247.3 2043.82  3462.4 2028.29  3579.2 2024.33  3725.0 2022.48
  3995.1 2017.89  4138.5 2018.15  4179.5 2016.17  4442.4 2016.10  4458.5 2016.50
  4882.4 2018.59  4958.0 2007.10  4968.2 2004.01  4979.8 1995.57  4983.1 1997.07
  4984.6 1995.07  5003.3 1995.07  5004.7 1997.07  5006.1 2006.01  5020.3 2008.19
  5091.4 2008.28  5154.9 2003.35  5175.8 1998.09  5183.4 1998.70  5190.1 2002.82
  5204.3 2005.29  5216.6 2010.27  5253.6 2015.61  5324.7 2018.30  5991.0 2018.21
#Mann=8,-1,0
  3155.1    0.05       0  3579.2    0.12       0  3725.0    0.05       0
  4442.4     0.1       0  4458.5    0.05       0  4983.1    0.05       0
  5004.7    0.05       0  5216.6    0.05       0
Bank Sta=4983.1,5004.7
Exp/Cntr=0.3,0.1

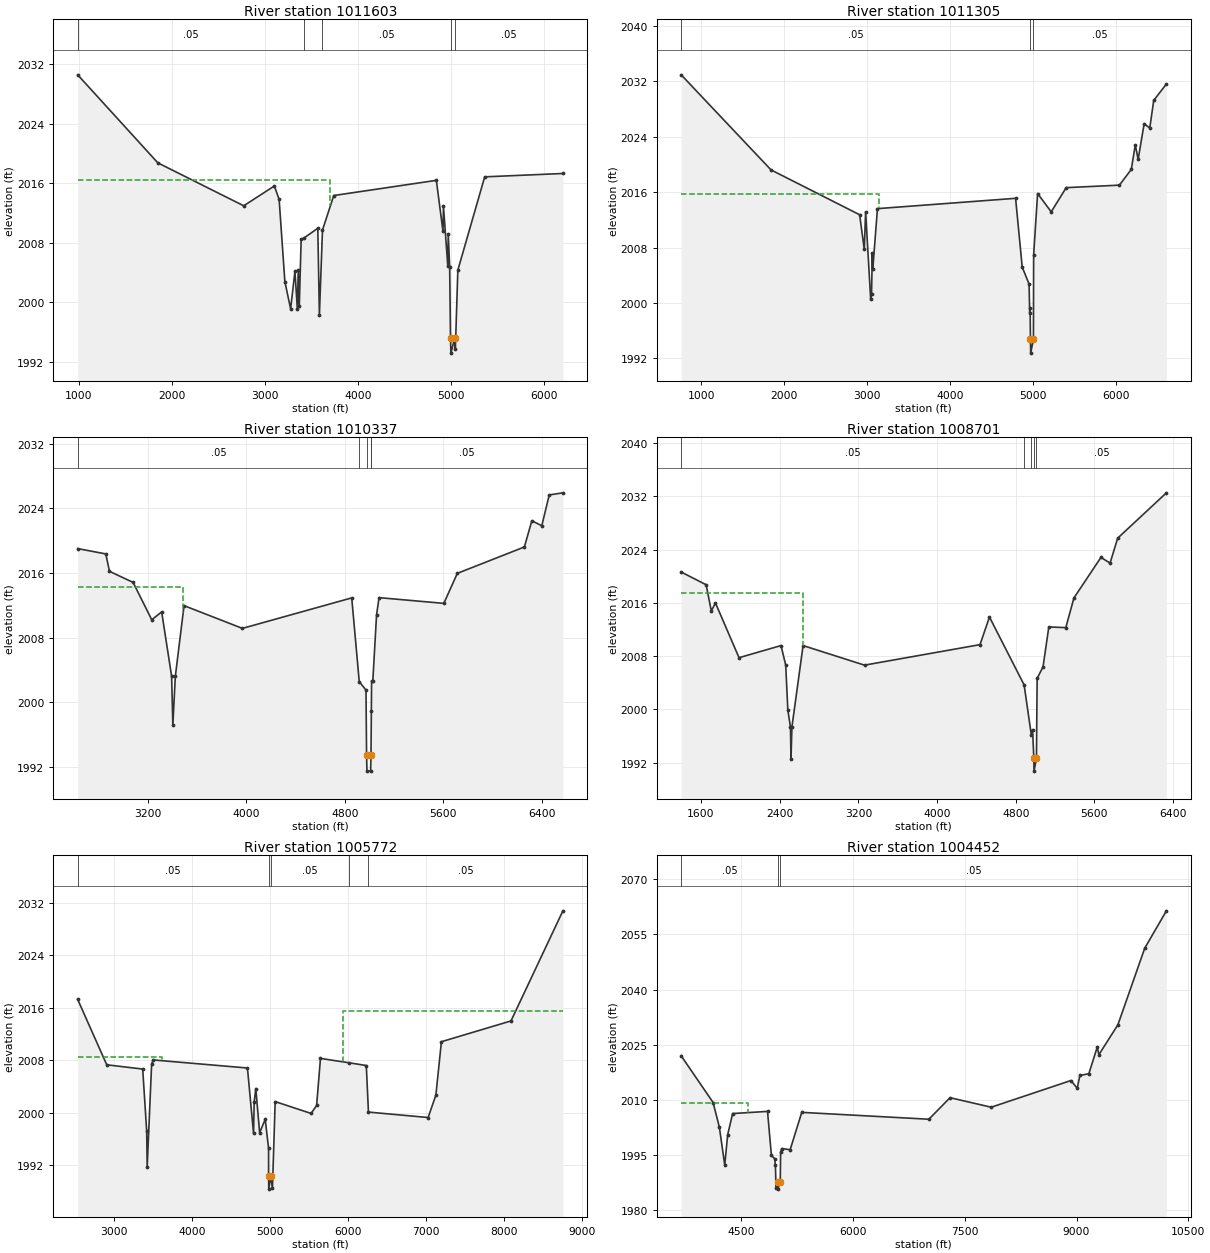
Type RM Length L Ch R = 1,1011603,298,298,298
BEGIN DESCRIPTION:
Mapping XS 9884f4c2
END DESCRIPTION:
XS GIS Cut Line= 6
      1330832.87      6974267.85      1331104.81      6973102.41
      1331289.03      6972312.92      1331677.19      6970780.01
      1331756.14      6970464.22      1332005.97      6969182.18
#Sta/Elev= 30
   986.3 2030.58  1848.7 2018.75  2772.9 2012.98  3102.0 2015.64  3153.6 2013.85
  3215.5 2002.78  3277.3 1999.13  3323.7 2004.18  3349.6 1999.15  3359.5 2004.34
  3370.2 1999.50  3390.8 2008.46  3419.6 2008.64  3569.7 2009.96  3586.8 1998.31
  3620.1 2009.72  3741.5 2014.36  4845.1 2016.40  4916.4 2009.56  4921.5 2012.92
  4968.0 2004.92  4973.1 2009.18  4988.4 2004.72  4997.5 1995.18  5001.4 1993.18
  5042.5 1995.18  5049.5 1993.68  5076.3 2004.33  5365.3 2016.87  6206.7 2017.32
#Mann=5,-1,0
   986.3    0.05       0  3419.6    0.12       0  3620.1    0.05       0
  4997.5    0.03       0  5042.5    0.05       0
#XS Ineff=2,0
    0.00 3704.50 2016.50               0
Permanent Ineff=
       F       F
Bank Sta=4997.5,5042.5
Exp/Cntr=0.3,0.1

Type RM Length L Ch R = 1,1011305,968,968,968
BEGIN DESCRIPTION:
Mapping XS 884ecbdb
END DESCRIPTION:
XS GIS Cut Line= 4
      1331169.05      6974347.87      1331387.98      6973248.85
      1331930.51      6970525.32      1332375.38      6968626.49
#Sta/Elev= 30
   760.3 2032.93  1843.1 2019.21  2910.8 2012.74  2966.9 2007.76  2983.0 2013.17
  3044.2 2000.54  3054.4 2001.36  3064.0 2007.21  3069.1 2004.86  3125.7 2013.62
  4790.5 2015.11  4870.3 2005.19  4953.1 2002.74  4960.4 1998.56  4965.5 1999.26
  4969.6 1994.77  4972.6 1992.77  5005.6 1994.77  5008.0 2006.91  5055.8 2015.80
  5220.1 2013.16  5400.4 2016.65  6041.8 2017.01  6185.2 2019.29  6232.8 2022.81
  6267.7 2020.74  6339.6 2025.85  6407.8 2025.27  6455.4 2029.24  6608.2 2031.61
#Mann=3,-1,0
   760.3    0.05       0  4969.6    0.03       0  5005.6    0.05       0
#XS Ineff=2,0
    0.00 3149.90 2015.76               0
Permanent Ineff=
       F       F
Bank Sta=4969.6,5005.6
Exp/Cntr=0.3,0.1

Type RM Length L Ch R = 1,1010337,1636,1636,1636
BEGIN DESCRIPTION:
Mapping XS f57cb7ff
END DESCRIPTION:
XS GIS Cut Line= 2
      1332494.75      6972934.18      1333058.99      6969027.92
#Sta/Elev= 30
  2627.2 2019.02  2855.7 2018.36  2886.0 2016.20  3078.0 2014.83  3229.6 2010.20
  3310.4 2011.17  3391.2 2003.21  3401.3 1997.13  3421.5 2003.18  3492.3 2011.95
  3967.1 2009.13  4856.3 2012.91  4917.4 2002.53  4972.4 2001.48  4977.0 1993.44
  4980.1 1991.44  5010.0 1991.44  5013.0 1993.44  5015.9 1998.88  5017.9 2002.63
  5028.0 2002.67  5058.4 2010.84  5078.6 2012.94  5605.4 2012.23  5715.1 2015.95
  6260.7 2019.22  6321.3 2022.47  6402.2 2021.85  6462.8 2025.67  6574.0 2025.93
#Mann=5,-1,0
  2627.2    0.05       0  4917.4     0.1       0  4977.0    0.07       0
  5013.0     0.1       0  5015.9    0.05       0
#XS Ineff=2,0
    0.00 3484.60 2014.23               0
Permanent Ineff=
       F       F
Bank Sta=4977,5013
Exp/Cntr=0.3,0.1

Type RM Length L Ch R = 1,1008701,2929,2929,2929
BEGIN DESCRIPTION:
Mapping XS 7ff4d2e6
END DESCRIPTION:
XS GIS Cut Line= 3
      1333178.34      6973129.51      1334148.72      6970123.36
      1333471.69      6968482.87
#Sta/Elev= 30
  1398.5 2020.63  1652.3 2018.72  1704.8 2014.78  1746.9 2015.99  1986.6 2007.77
  2413.6 2009.59  2461.4 2006.66  2482.9 1999.92  2509.7 1997.36  2515.0 1992.56
  2524.5 1997.37  2637.9 2009.59  3262.4 2006.65  4436.9 2009.73  4532.9 2013.87
  4885.4 2003.68  4958.9 1996.14  4971.2 1996.97  4983.9 1992.74  4986.2 1990.74
  5010.9 1992.74  5017.6 2004.66  5077.7 2006.40  5136.6 2012.39  5309.2 2012.28
  5391.8 2016.74  5666.6 2022.83  5759.2 2021.97  5836.4 2025.71  6332.1 2032.52
#Mann=5,-1,0
  1398.5    0.05       0  4885.4     0.1       0  4958.9    0.05       0
  4983.9    0.05       0  5010.9    0.05       0
#XS Ineff=2,0
    0.00 2640.40 2017.48 7359.60    0.00 2017.48
Permanent Ineff=
       F       F
Bank Sta=4983.9,5010.9
Exp/Cntr=0.3,0.1

Type RM Length L Ch R = 1,1005772,1320,1320,1320
BEGIN DESCRIPTION:
Clear Fork Brazos Rv 275.0
END DESCRIPTION:
XS GIS Cut Line= 3
      1333289.34      6972996.63      1334877.89      6971095.58
      1337605.03      6968537.97
#Sta/Elev= 30
  2535.5 2017.28  2908.0 2007.31  3368.7 2006.66  3419.4 1997.20  3425.9 1991.74
  3483.2 2007.48  3504.0 2008.05  4710.4 2006.82  4788.5 1996.84  4796.3 2001.60
  4817.1 2003.69  4866.6 1996.96  4938.1 1999.00  4981.1 1994.58  4981.4 1990.35
  4983.7 1988.35  5008.4 1990.35  5030.4 1988.45  5065.6 2001.70  5525.7 1999.89
  5596.5 2001.11  5645.8 2008.28  6005.3 2007.63  6233.0 2007.20  6260.5 2000.10
  7025.2 1999.27  7124.4 2002.69  7195.2 2010.83  8086.6 2014.00  8751.7 2030.79
#Mann=5,-1,0
  2535.5    0.05       0  4981.4    0.05       0  5008.4    0.05       0
  6005.3    0.12       0  6260.5    0.05       0
#XS Ineff=2,0
    0.00 3609.60 2008.44 5935.70    0.00 2015.50
Permanent Ineff=
       F       F
Bank Sta=4981.4,5008.4
Exp/Cntr=0.3,0.1

Type RM Length L Ch R = 1,1004452,2208,2208,2208
BEGIN DESCRIPTION:
Clear Fork Brazos Rv 274.0
END DESCRIPTION:
XS GIS Cut Line= 3
      1334278.95      6973369.86      1334851.85      6972232.73
      1338304.98      6968288.02
#Sta/Elev= 30
  3691.2 2021.98  4120.1 2009.27  4203.7 2002.58  4276.3 1992.24  4315.3 2000.50
  4382.2 2006.28  4850.7 2006.86  4902.6 1994.92  4947.4 1993.98  4956.7 1992.21
  4964.3 1986.10  4986.0 1987.72  4989.1 1985.72  5022.0 1987.72  5026.5 1995.73
  5040.7 1996.76  5154.6 1996.44  5310.3 2006.60  7017.7 2004.73  7301.5 2010.59
  7854.8 2008.00  8924.4 2015.26  9009.8 2013.17  9045.0 2016.63  9165.5 2017.11
  9278.4 2024.35  9300.3 2022.29  9555.6 2030.42  9916.2 2051.27 10207.1 2061.42
#Mann=3,-1,0
  3691.2    0.05       0  4986.0    0.05       0  5022.0    0.05       0
#XS Ineff=2,0
    0.00 4589.90 2009.13               0
Permanent Ineff=
       F       F
Bank Sta=4986,5022
Exp/Cntr=0.3,0.1

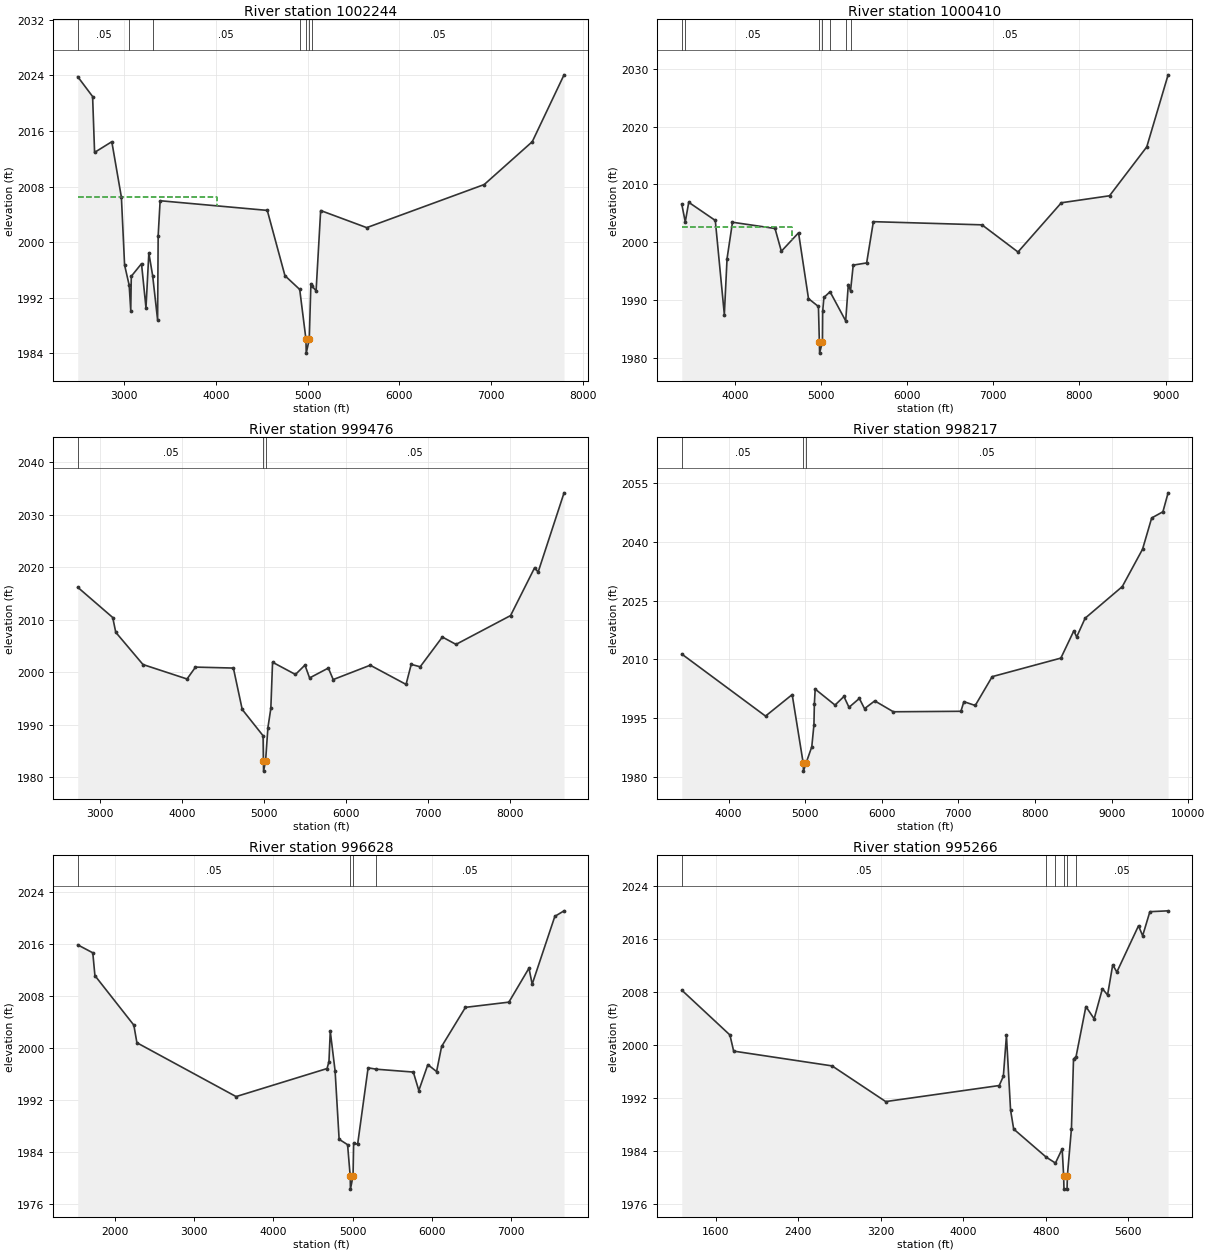
Type RM Length L Ch R = 1,1002244,1834,1834,1834
BEGIN DESCRIPTION:
Clear Fork Brazos Rv 273.0
END DESCRIPTION:
XS GIS Cut Line= 3
      1334804.97      6973288.02      1336596.64      6972232.73
      1338804.99      6969888.01
#Sta/Elev= 30
  2495.6 2023.81  2657.7 2020.96  2679.2 2012.92  2867.0 2014.46  2971.5 2006.47
  3006.3 1996.72  3056.2 1993.82  3073.5 1990.18  3079.3 1995.10  3190.7 1996.92
  3239.4 1990.56  3270.7 1998.45  3312.3 1995.18  3366.1 1988.82  3372.2 2000.94
  3393.6 2005.97  4561.4 2004.58  4754.0 1995.19  4914.9 1993.21  4982.9 1986.05
  4986.0 1984.05  5018.9 1986.05  5036.8 1994.03  5049.2 1993.69  5093.5 1993.01
  5143.2 2004.56  5645.3 2002.10  6925.9 2008.30  7449.4 2014.46  7795.9 2024.08
#Mann=7,-1,0
  2495.6    0.05       0  3056.2    0.12       0  3312.3    0.05       0
  4914.9     0.1       0  4982.9    0.07       0  5018.9     0.1       0
  5049.2    0.05       0
#XS Ineff=2,0
    0.00 4017.40 2006.47               0
Permanent Ineff=
       F       F
Bank Sta=4982.9,5018.9
Exp/Cntr=0.3,0.1

Type RM Length L Ch R = 1,1000410,934,934,934
BEGIN DESCRIPTION:
Clear Fork Brazos Rv 272.0
END DESCRIPTION:
XS GIS Cut Line= 3
      1335174.85      6973878.19      1336705.00      6973388.00
      1339404.98      6970388.03
#Sta/Elev= 30
  3385.6 2006.57  3426.0 2003.52  3466.3 2006.91  3774.3 2003.77  3879.3 1987.49
  3910.8 1997.16  3973.8 2003.46  4467.3 2002.38  4540.8 1998.44  4740.3 2001.63
  4855.8 1990.24  4971.0 1988.88  4981.8 1982.81  4984.8 1980.81  5017.8 1982.81
  5020.4 1988.03  5034.6 1990.44  5106.0 1991.43  5287.3 1986.39  5317.8 1992.68
  5343.5 1991.57  5374.7 1996.04  5530.5 1996.42  5608.6 2003.56  6868.8 2003.01
  7286.6 1998.31  7789.6 2006.83  8348.7 2008.04  8780.7 2016.50  9028.4 2028.97
#Mann=7,-1,0
  3385.6    0.12       0  3426.0    0.05       0  4981.8    0.07       0
  5017.8    0.05       0  5106.0    0.05       0  5287.3    0.12       0
  5343.5    0.05       0
#XS Ineff=2,0
    0.00 4660.10 2002.55               0
Permanent Ineff=
       F       F
Bank Sta=4981.8,5017.8
Exp/Cntr=0.3,0.1

Type RM Length L Ch R = 1,999476,1259,1259,1259
BEGIN DESCRIPTION:
Clear Fork Brazos Rv 271.0
END DESCRIPTION:
XS GIS Cut Line= 3
      1336845.87      6975505.80      1337555.00      6973338.00
      1339655.00      6970338.00
#Sta/Elev= 30
  2722.9 2016.17  3150.5 2010.42  3187.6 2007.61  3520.2 2001.48  4058.5 1998.73
  4162.0 2000.99  4625.0 2000.81  4732.9 1992.94  4987.8 1987.94  4991.7 1983.21
  4993.9 1981.21  5018.7 1983.21  5046.9 1989.48  5082.6 1993.13  5103.6 2001.92
  5383.4 1999.59  5499.4 2001.37  5556.1 1998.93  5785.4 2000.81  5844.7 1998.62
  6297.2 2001.35  6734.9 1997.70  6798.1 2001.51  6907.5 2001.05  7178.7 2006.71
  7345.2 2005.31  8012.2 2010.79  8306.9 2019.91  8348.8 2019.05  8665.7 2034.13
#Mann=3,-1,0
  2722.9    0.05       0  4991.7    0.07       0  5018.7    0.05       0
Bank Sta=4991.7,5018.7
Exp/Cntr=0.3,0.1

Type RM Length L Ch R = 1,998217,1589,1589,1589
BEGIN DESCRIPTION:
Clear Fork Brazos Rv 270.0
END DESCRIPTION:
XS GIS Cut Line= 3
      1337193.07      6975484.12      1338180.80      6974284.52
      1340405.02      6970037.96
#Sta/Elev= 30
  3389.8 2011.37  4482.8 1995.58  4830.7 2001.05  4974.9 1983.57  4977.9 1981.57
  5010.9 1983.57  5086.5 1987.76  5114.6 1993.34  5120.4 1998.76  5131.0 2002.45
  5390.1 1998.38  5506.1 2000.57  5572.3 1997.81  5707.4 2000.07  5775.1 1997.47
  5908.4 1999.45  6151.1 1996.68  7033.2 1996.80  7071.7 1999.25  7220.1 1998.28
  7441.2 2005.62  8337.7 2010.34  8507.0 2017.28  8543.9 2015.73  8654.2 2020.49
  9139.1 2028.54  9403.9 2038.06  9523.0 2046.01  9669.7 2047.59  9737.5 2052.41
#Mann=3,-1,0
  3389.8    0.05       0  4974.9    0.05       0  5010.9    0.05       0
Bank Sta=4974.9,5010.9
Exp/Cntr=0.3,0.1

Type RM Length L Ch R = 1,996628,1362,1362,1362
BEGIN DESCRIPTION:
Clear Fork Brazos Rv 269.0
END DESCRIPTION:
XS GIS Cut Line= 3
      1340187.02      6977065.07      1339447.88      6972771.06
      1340004.99      6971088.03
#Sta/Elev= 30
  1533.9 2015.82  1723.7 2014.60  1750.6 2011.10  2241.2 2003.50  2279.7 2000.80
  3529.9 1992.54  4676.5 1996.84  4700.7 1997.92  4717.1 2002.56  4778.0 1996.47
  4828.7 1985.99  4935.3 1985.16  4968.3 1980.34  4971.3 1978.34  5004.3 1980.34
  5011.4 1985.38  5062.1 1985.23  5194.0 1996.95  5298.0 1996.74  5764.0 1996.30
  5833.3 1993.47  5947.0 1997.44  6057.2 1996.38  6120.7 2000.23  6421.0 2006.23
  6968.7 2007.03  7221.5 2012.24  7262.3 2009.79  7547.7 2020.19  7663.9 2021.04
#Mann=4,-1,0
  1533.9    0.05       0  4968.3    0.07       0  5004.3    0.05       0
  5298.0    0.05       0
Bank Sta=4968.3,5004.3
Exp/Cntr=0.3,0.1

Type RM Length L Ch R = 1,995266,1219,1219,1219
BEGIN DESCRIPTION:
Clear Fork Brazos Rv 268.0
END DESCRIPTION:
XS GIS Cut Line= 2
      1340600.22      6976764.49      1340785.30      6972051.22
#Sta/Elev= 30
  1269.9 2008.25  1736.8 2001.49  1772.9 1999.06  2727.5 1996.83  3247.9 1991.45
  4348.8 1993.87  4388.8 1995.27  4418.8 2001.42  4458.8 1990.17  4488.9 1987.31
  4804.5 1983.07  4894.1 1982.18  4959.2 1984.32  4973.7 1980.25  4976.7 1978.25
  5006.7 1978.25  5009.7 1980.25  5049.3 1987.39  5069.3 1997.87  5094.1 1998.24
  5189.4 2005.78  5269.5 2003.93  5349.5 2008.47  5399.6 2007.52  5449.6 2012.07
  5489.6 2010.98  5699.8 2017.96  5739.8 2016.45  5809.9 2020.08  5986.8 2020.21
#Mann=6,-1,0
  1269.9    0.05       0  4804.5    0.12       0  4894.1    0.05       0
  4973.7    0.07       0  5009.7    0.05       0  5094.1    0.05       0
Bank Sta=4973.7,5009.7
Exp/Cntr=0.3,0.1