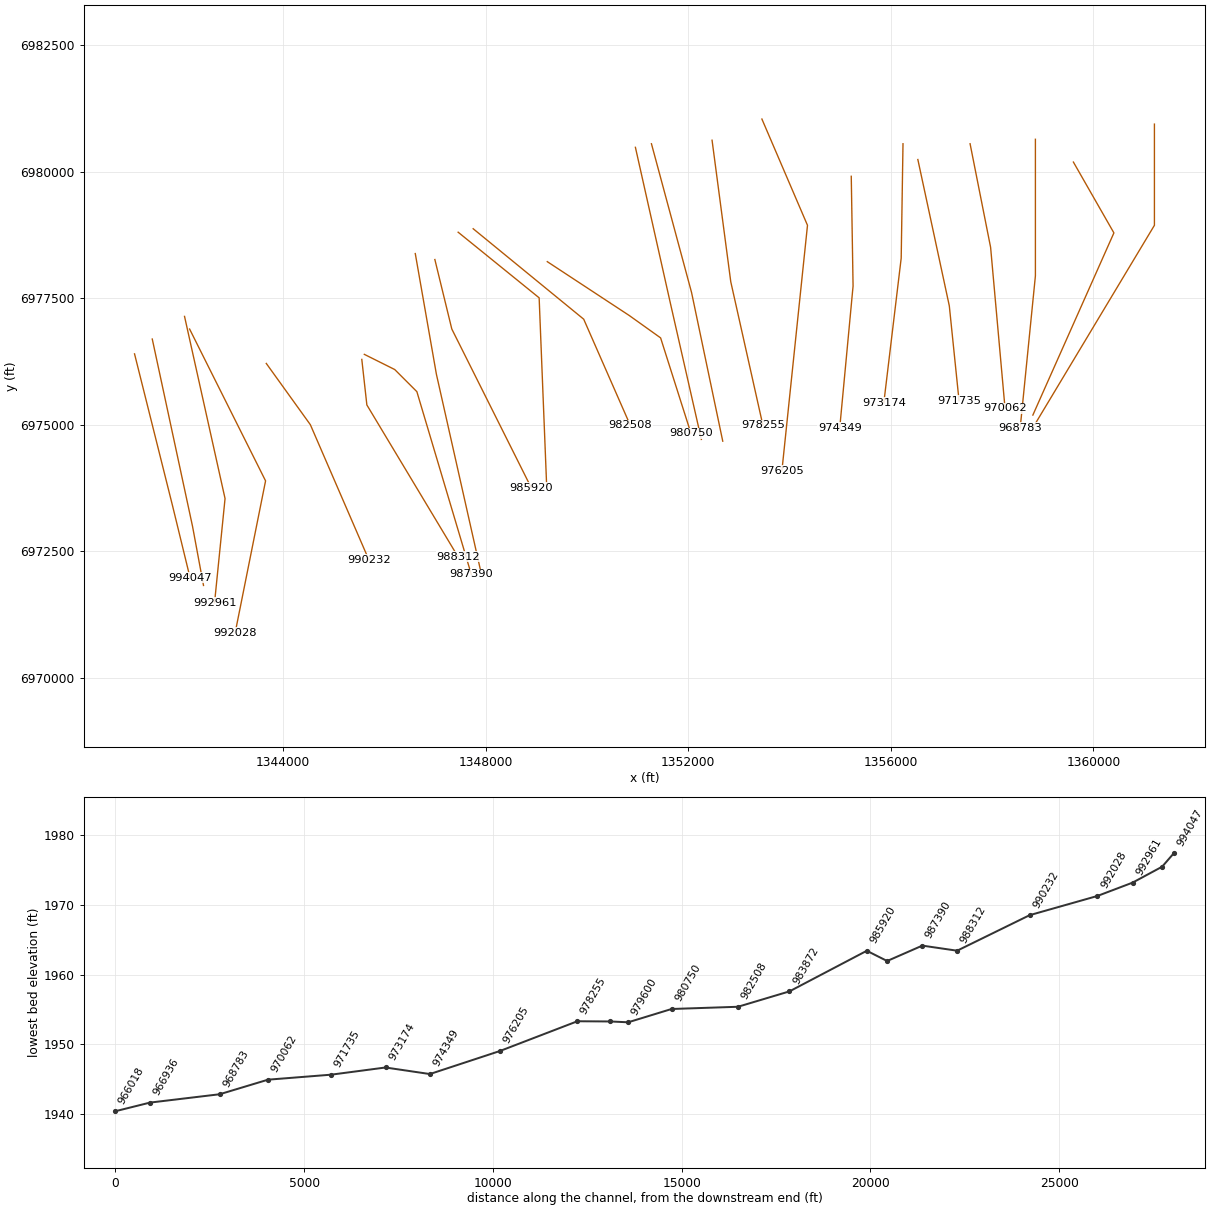
HEC-RAS study Clear Fork Brazos Rv.prj: Clear Fork Brazos Rv Base Level Engineering

--- Clear Fork Brazos Rv.g01 (geometry) --- (continued)

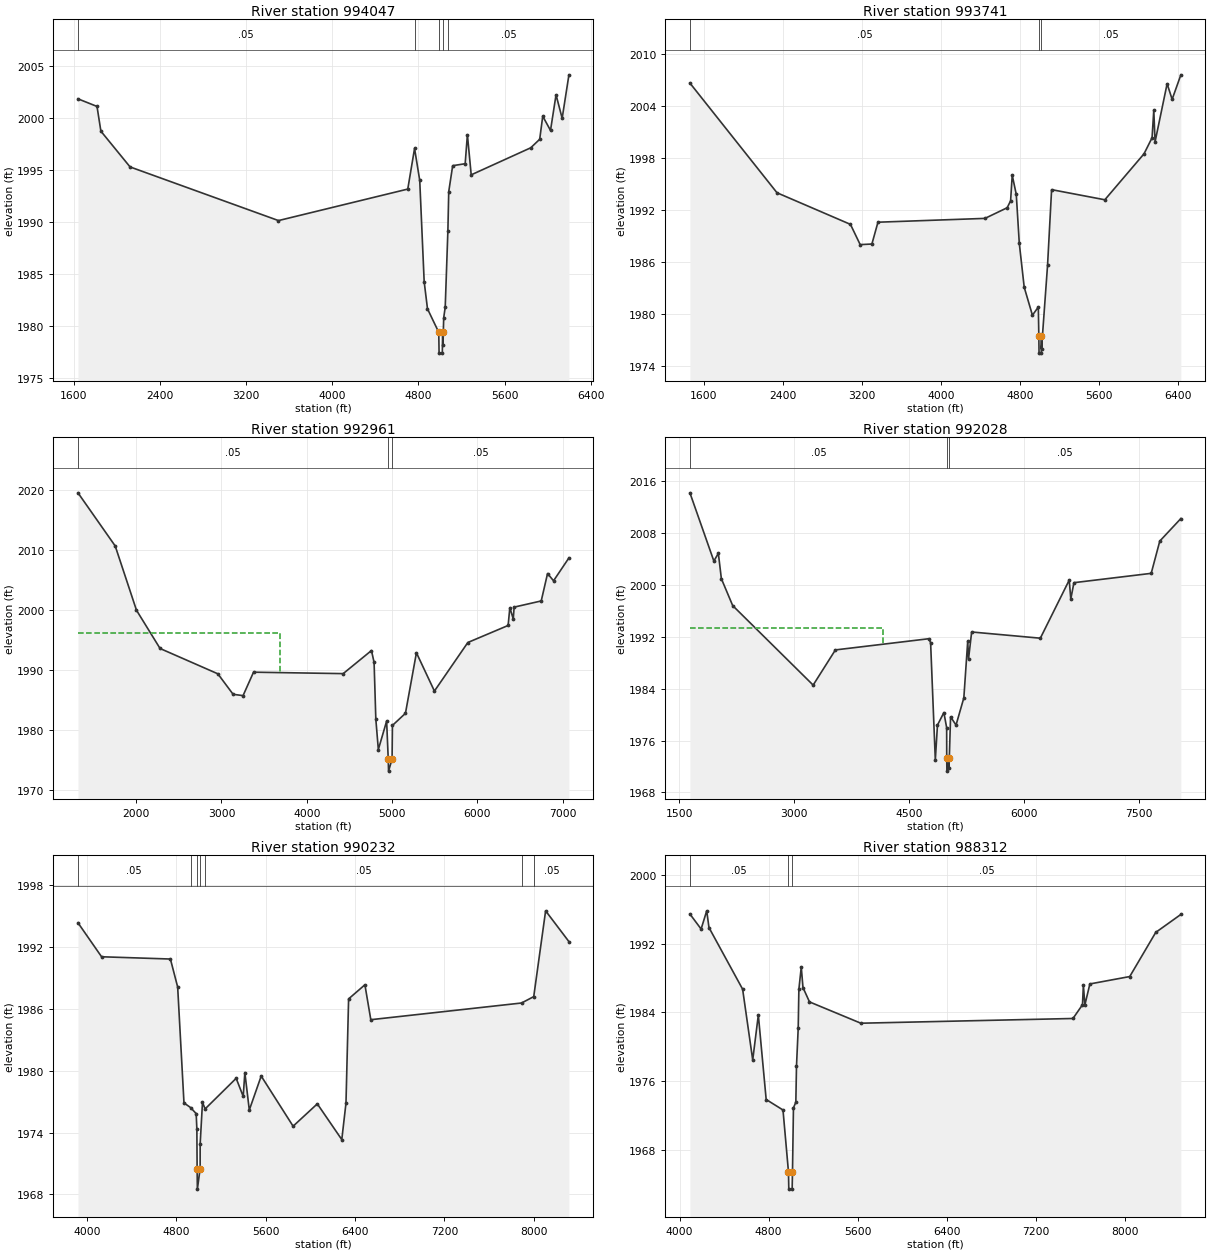
Type RM Length L Ch R = 1,994047,306,306,306
BEGIN DESCRIPTION:
Mapping XS e155350b
END DESCRIPTION:
XS GIS Cut Line= 3
      1341067.83      6976397.48      1341815.14      6973408.27
      1342164.82      6971971.73
#Sta/Elev= 30
  1638.4 2001.85  1815.3 2001.12  1851.3 1998.74  2122.3 1995.30  3500.6 1990.14
  4701.4 1993.17  4764.5 1997.08  4812.5 1994.00  4853.7 1984.26  4884.6 1981.65
  4989.2 1979.39  4992.2 1977.39  5022.2 1977.39  5025.2 1979.39  5028.6 1978.20
  5035.0 1980.78  5049.2 1981.81  5074.0 1989.18  5081.8 1992.92  5118.4 1995.42
  5234.5 1995.61  5255.1 1998.40  5290.5 1994.54  5843.2 1997.14  5926.6 1997.96
  5954.9 2000.18  6027.0 1998.81  6078.4 2002.24  6135.2 1999.98  6198.1 2004.16
#Mann=5,-1,0
  1638.4    0.05       0  4764.5    0.12       0  4989.2    0.07       0
  5025.2    0.12       0  5074.0    0.05       0
Bank Sta=4989.2,5025.2
Exp/Cntr=0.3,0.1

Type RM Length L Ch R = 1,993741,780,780,780
BEGIN DESCRIPTION:
Mapping XS a04bfabd
END DESCRIPTION:
XS GIS Cut Line= 3
      1341417.84      6976690.68      1342212.43      6972992.05
      1342429.64      6971821.04
#Sta/Elev= 30
  1457.4 2006.67  2339.8 1994.00  3083.9 1990.35  3182.6 1988.01  3301.2 1988.08
  3362.6 1990.60  4446.8 1991.04  4671.8 1992.27  4706.4 1993.07  4722.9 1996.02
  4763.8 1993.82  4794.5 1988.15  4844.3 1983.09  4927.5 1979.86  4987.3 1980.80
  4992.4 1977.48  4994.6 1975.48  5017.1 1975.48  5019.4 1977.48  5019.5 1975.98
  5080.9 1985.64  5121.8 1994.36  5661.1 1993.19  6058.2 1998.50  6139.6 2000.35
  6157.0 2003.53  6170.1 1999.89  6292.1 2006.59  6343.0 2004.79  6431.4 2007.62
#Mann=3,-1,0
  1457.4    0.05       0  4992.4    0.05       0  5019.4    0.05       0
Bank Sta=4992.4,5019.4
Exp/Cntr=0.3,0.1

Type RM Length L Ch R = 1,992961,933,933,933
BEGIN DESCRIPTION:
Clear Fork Brazos Rv 266.0
END DESCRIPTION:
XS GIS Cut Line= 3
      1342055.01      6977137.97      1342855.00      6973538.00
      1342647.56      6971478.51
#Sta/Elev= 30
  1317.5 2019.61  1754.1 2010.75  2003.8 2000.03  2280.4 1993.65  2957.8 1989.43
  3137.1 1986.01  3253.6 1985.79  3376.5 1989.70  4427.8 1989.46  4759.4 1993.31
  4790.2 1991.34  4810.7 1981.85  4840.1 1976.80  4937.4 1981.55  4956.2 1975.20
  4959.9 1973.20  5001.2 1975.20  5005.3 1980.82  5158.0 1982.84  5286.7 1992.94
  5497.8 1986.55  5889.7 1994.65  6362.1 1997.49  6382.2 2000.45  6422.4 1998.59
  6432.5 2000.55  6750.3 2001.58  6824.4 2006.15  6894.8 2004.94  7075.2 2008.76
#Mann=3,-1,0
  1317.5    0.05       0  4956.2    0.03       0  5001.2    0.05       0
#XS Ineff=2,0
    0.00 3690.10 1996.31               0
Permanent Ineff=
       F       F
Bank Sta=4956.2,5001.2
Exp/Cntr=0.3,0.1

Type RM Length L Ch R = 1,992028,1796,1796,1796
BEGIN DESCRIPTION:
Clear Fork Brazos Rv 265.0
END DESCRIPTION:
XS GIS Cut Line= 3
      1342155.01      6976887.98      1343655.00      6973888.00
      1343055.00      6970887.99
#Sta/Elev= 30
  1638.4 2014.24  1951.4 2003.71  2010.1 2004.90  2049.3 2000.99  2197.4 1996.83
  3248.3 1984.56  3539.0 1989.99  4760.5 1991.72  4782.8 1991.10  4844.3 1972.99
  4872.3 1978.39  4956.1 1980.32  4992.5 1977.98  4993.4 1973.28  4995.7 1971.28
  5020.4 1973.28  5023.1 1971.78  5043.5 1979.66  5114.9 1978.39  5216.8 1982.59
  5267.8 1991.37  5278.0 1988.58  5318.8 1992.76  6216.2 1991.80  6593.6 2000.77
  6614.0 1997.84  6654.8 2000.37  7664.4 2001.81  7776.5 2006.79  8051.9 2010.27
#Mann=3,-1,0
  1638.4    0.05       0  4993.4    0.05       0  5020.4    0.05       0
#XS Ineff=2,0
    0.00 4159.60 1993.40               0
Permanent Ineff=
       F       F
Bank Sta=4993.4,5020.4
Exp/Cntr=0.3,0.1

Type RM Length L Ch R = 1,990232,1920,1920,1920
BEGIN DESCRIPTION:
Mapping XS fafb45da
END DESCRIPTION:
XS GIS Cut Line= 3
      1343669.20      6976208.25      1344539.46      6974997.46
      1345692.84      6972331.45
#Sta/Elev= 30
  3919.1 1994.38  4130.5 1991.08  4746.8 1990.86  4811.8 1988.14  4868.3 1976.89
  4927.3 1976.44  4977.6 1975.85  4983.7 1974.34  4986.0 1970.52  4988.3 1968.52
  5013.0 1970.52  5013.2 1972.91  5034.0 1976.94  5057.8 1976.31  5335.6 1979.28
  5398.7 1977.52  5413.3 1979.84  5453.2 1976.20  5559.7 1979.50  5845.4 1974.63
  6062.1 1976.80  6281.3 1973.33  6318.8 1976.87  6342.3 1986.99  6488.3 1988.36
  6541.1 1984.97  7890.6 1986.59  7999.9 1987.21  8106.3 1995.54  8315.0 1992.55
#Mann=7,-1,0
  3919.1    0.05       0  4927.3    0.12       0  4986.0    0.07       0
  5013.0    0.12       0  5057.8    0.05       0  7890.6    0.12       0
  7999.9    0.05       0
Bank Sta=4986,5013
Exp/Cntr=0.3,0.1

Type RM Length L Ch R = 1,988312,922,922,922
BEGIN DESCRIPTION:
Clear Fork Brazos Rv 263.0
END DESCRIPTION:
XS GIS Cut Line= 3
      1345555.00      6976288.02      1345655.00      6975388.00
      1347454.99      6972388.02
#Sta/Elev= 30
  4093.3 1995.44  4193.9 1993.69  4244.2 1995.81  4264.4 1993.86  4566.2 1986.69
  4656.8 1978.45  4707.1 1983.69  4777.5 1973.85  4928.4 1972.63  4977.5 1965.42
  4980.5 1963.42  5010.5 1963.42  5013.5 1965.42  5022.2 1972.87  5043.6 1973.55
  5049.4 1977.72  5064.9 1982.17  5070.8 1986.67  5092.2 1989.26  5107.7 1986.88
  5166.0 1985.21  5626.7 1982.73  7529.5 1983.28  7615.0 1984.88  7622.8 1987.16
  7636.4 1984.86  7681.1 1987.30  8038.7 1988.16  8272.0 1993.30  8497.4 1995.39
#Mann=3,-1,0
  4093.3    0.05       0  4977.5    0.05       0  5013.5    0.05       0
Bank Sta=4977.5,5013.5
Exp/Cntr=0.3,0.1

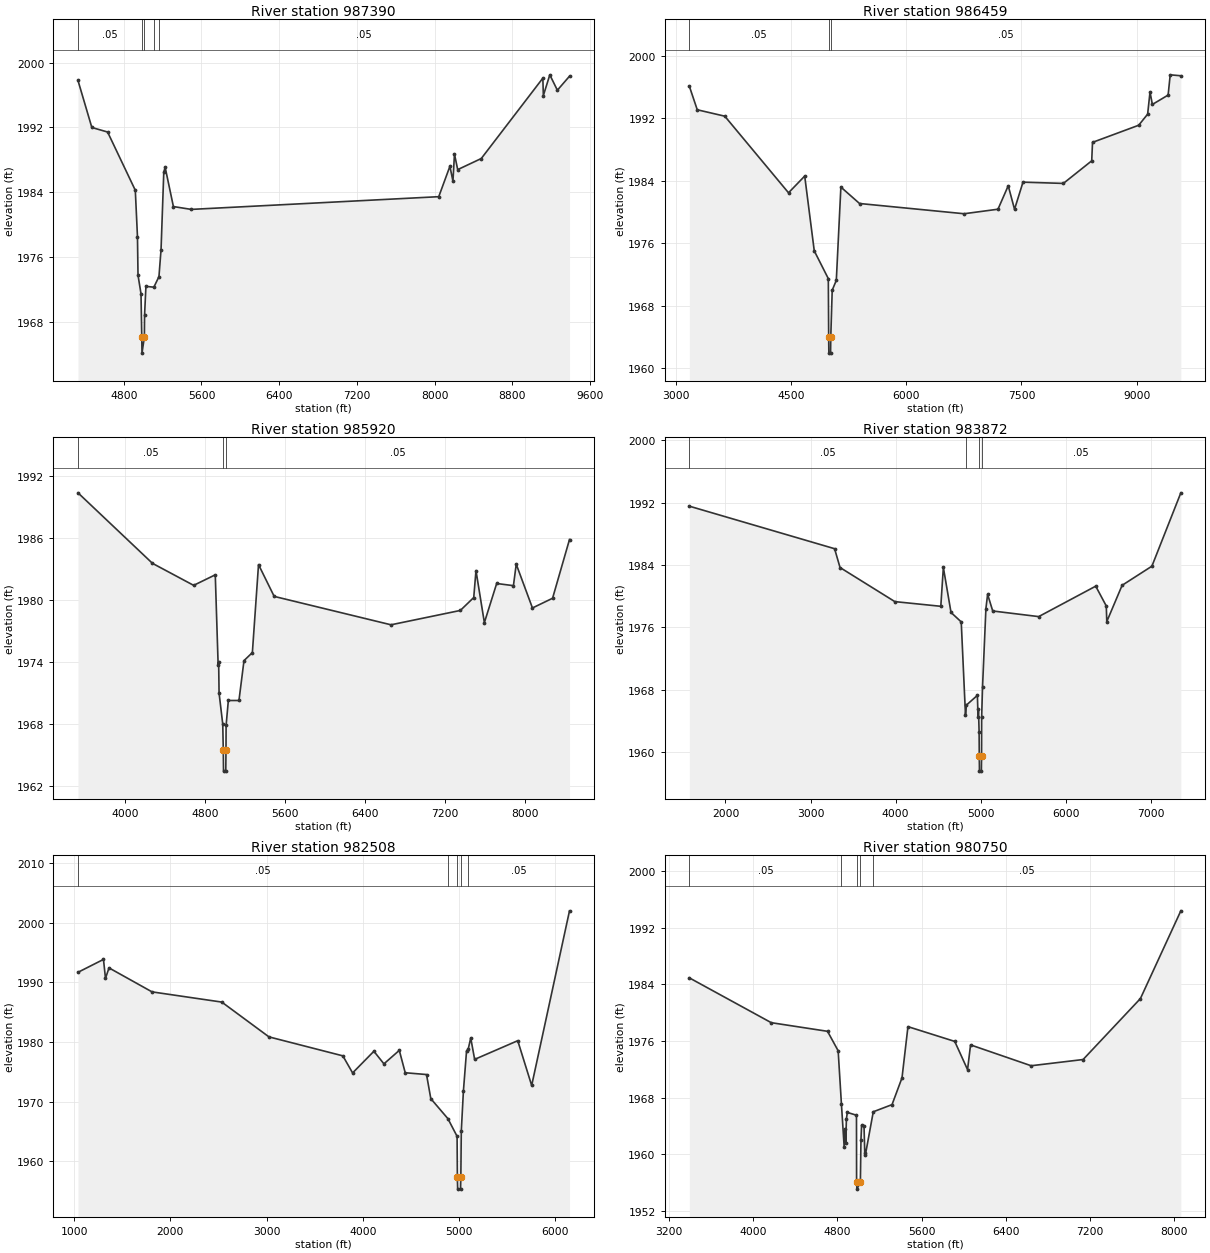
Type RM Length L Ch R = 1,987390,931,931,931
BEGIN DESCRIPTION:
Clear Fork Brazos Rv 262.0
END DESCRIPTION:
XS GIS Cut Line= 4
      1345605.00      6976388.00      1346205.00      6976088.00
      1346642.43      6975650.57      1347717.74      6972038.37
#Sta/Elev= 30
  4329.4 1997.80  4471.9 1992.00  4634.1 1991.44  4919.2 1984.25  4941.5 1978.53
  4947.1 1973.77  4977.9 1971.48  4985.7 1966.15  4988.0 1964.15  5012.7 1966.15
  5014.4 1968.80  5028.5 1972.39  5110.2 1972.29  5162.6 1973.59  5184.1 1976.92
  5212.4 1986.51  5226.5 1987.08  5311.3 1982.24  5495.2 1981.89  8042.1 1983.46
  8156.9 1987.21  8188.2 1985.38  8203.9 1988.72  8237.1 1986.80  8479.7 1988.17
  9113.4 1998.09  9118.6 1995.94  9185.0 1998.50  9262.9 1996.60  9387.7 1998.33
#Mann=5,-1,0
  4329.4    0.05       0  4985.7    0.05       0  5012.7    0.05       0
  5110.2     0.1       0  5162.6    0.05       0
Bank Sta=4985.7,5012.7
Exp/Cntr=0.3,0.1

Type RM Length L Ch R = 1,986459,539,539,539
BEGIN DESCRIPTION:
Mapping XS 5fd769a9
END DESCRIPTION:
XS GIS Cut Line= 3
      1346610.96      6978379.55      1347027.63      6975996.70
      1347900.01      6972116.57
#Sta/Elev= 30
  3178.3 1996.09  3281.4 1993.07  3639.5 1992.25  4469.1 1982.45  4679.7 1984.59
  4804.1 1975.02  4986.9 1971.47  4991.7 1963.94  4993.9 1961.94  5016.4 1961.94
  5018.7 1963.94  5037.6 1969.99  5091.0 1971.25  5150.5 1983.18  5393.0 1981.08
  6754.2 1979.77  7194.9 1980.35  7328.2 1983.35  7410.2 1980.34  7520.3 1983.81
  8045.6 1983.65  8414.6 1986.54  8424.9 1988.90  9025.8 1991.09  9142.3 1992.51
  9173.1 1995.34  9203.8 1993.75  9408.8 1994.95  9436.0 1997.54  9574.3 1997.42
#Mann=3,-1,0
  3178.3    0.05       0  4991.7    0.05       0  5018.7    0.05       0
Bank Sta=4991.7,5018.7
Exp/Cntr=0.3,0.1

Type RM Length L Ch R = 1,985920,2048,2048,2048
BEGIN DESCRIPTION:
Clear Fork Brazos Rv 261.0
END DESCRIPTION:
XS GIS Cut Line= 3
      1346997.60      6978261.77      1347331.97      6976889.09
      1348898.24      6973756.55
#Sta/Elev= 30
  3530.2 1990.36  4275.1 1983.53  4686.8 1981.40  4903.0 1982.42  4931.7 1973.71
  4936.8 1973.96  4941.0 1970.97  4977.8 1967.96  4983.2 1965.41  4985.5 1963.41
  5008.0 1963.41  5010.2 1965.41  5011.3 1967.83  5033.7 1970.25  5139.9 1970.25
  5190.2 1974.11  5274.0 1974.89  5335.5 1983.41  5492.1 1980.33  6660.4 1977.58
  7353.6 1978.97  7487.7 1980.22  7510.1 1982.83  7594.0 1977.79  7717.0 1981.58
  7884.6 1981.37  7912.6 1983.45  8074.7 1979.21  8276.0 1980.15  8445.3 1985.84
#Mann=3,-1,0
  3530.2    0.05       0  4983.2    0.05       0  5010.2    0.05       0
Bank Sta=4983.2,5010.2
Exp/Cntr=0.3,0.1

Type RM Length L Ch R = 1,983872,1364,1364,1364
BEGIN DESCRIPTION:
Clear Fork Brazos Rv 260.0
END DESCRIPTION:
XS GIS Cut Line= 3
      1347457.35      6978801.77      1349056.62      6977505.03
      1349205.00      6973788.02
#Sta/Elev= 30
  1575.2 1991.53  3283.0 1986.08  3347.0 1983.67  3991.4 1979.30  4531.9 1978.70
  4561.9 1983.68  4652.0 1977.91  4772.1 1976.70  4822.1 1964.77  4832.9 1966.04
  4962.2 1967.29  4969.8 1964.46  4974.8 1965.56  4982.2 1962.61  4984.2 1959.58
  4986.4 1957.58  5008.9 1957.58  5011.2 1959.58  5012.3 1964.51  5022.3 1968.31
  5062.3 1978.41  5082.3 1980.23  5142.4 1978.10  5682.8 1977.38  6353.3 1981.28
  6477.5 1978.74  6483.4 1976.74  6663.6 1981.39  7013.8 1983.84  7354.1 1993.24
#Mann=4,-1,0
  1575.2    0.05       0  4832.9     0.1       0  4984.2    0.07       0
  5011.2    0.05       0
Bank Sta=4984.2,5011.2
Exp/Cntr=0.3,0.1

Type RM Length L Ch R = 1,982508,1758,1758,1758
BEGIN DESCRIPTION:
Clear Fork Brazos Rv 259.0
END DESCRIPTION:
XS GIS Cut Line= 3
      1347754.27      6978870.24      1349936.54      6977082.67
      1350854.99      6974988.02
#Sta/Elev= 30
  1039.7 1991.70  1304.6 1993.86  1325.4 1990.68  1362.0 1992.44  1809.2 1988.42
  2534.1 1986.71  3024.3 1980.88  3792.3 1977.70  3893.6 1974.84  4114.8 1978.47
  4219.2 1976.36  4378.9 1978.62  4440.5 1974.87  4661.8 1974.57  4706.5 1970.53
  4883.5 1967.19  4979.5 1964.22  4982.5 1957.37  4985.5 1955.37  5015.5 1955.37
  5018.5 1957.37  5023.2 1965.10  5045.1 1971.78  5077.8 1978.52  5094.6 1978.80
  5121.4 1980.69  5161.9 1977.11  5609.9 1980.24  5754.7 1972.74  6147.8 2002.00
#Mann=5,-1,0
  1039.7    0.05       0  4883.5     0.1       0  4982.5    0.07       0
  5018.5     0.1       0  5094.6    0.05       0
Bank Sta=4982.5,5018.5
Exp/Cntr=0.3,0.1

Type RM Length L Ch R = 1,980750,1150,1150,1150
BEGIN DESCRIPTION:
Mapping XS 45cf34ab
END DESCRIPTION:
XS GIS Cut Line= 4
      1349217.47      6978219.80      1350834.63      6977156.46
      1351454.90      6976713.41      1352052.61      6974831.75
#Sta/Elev= 30
  3392.1 1984.93  4171.0 1978.59  4705.6 1977.37  4806.7 1974.62  4838.0 1967.05
  4863.9 1961.03  4873.0 1963.61  4879.0 1961.51  4885.2 1965.00  4894.1 1965.90
  4980.9 1965.50  4982.0 1956.05  4985.0 1955.05  5018.0 1956.05  5023.6 1962.06
  5029.6 1964.09  5052.7 1963.93  5059.8 1960.13  5065.7 1959.91  5140.6 1965.99
  5318.8 1967.00  5413.7 1970.79  5470.2 1978.03  5915.1 1975.94  6036.7 1971.95
  6065.3 1975.45  6641.1 1972.50  7135.0 1973.38  7679.8 1982.00  8064.1 1994.41
#Mann=5,-1,0
  3392.1    0.05       0  4838.0    0.12       0  4982.0    0.07       0
  5018.0    0.12       0  5140.6    0.05       0
Bank Sta=4982,5018
Exp/Cntr=0.3,0.1

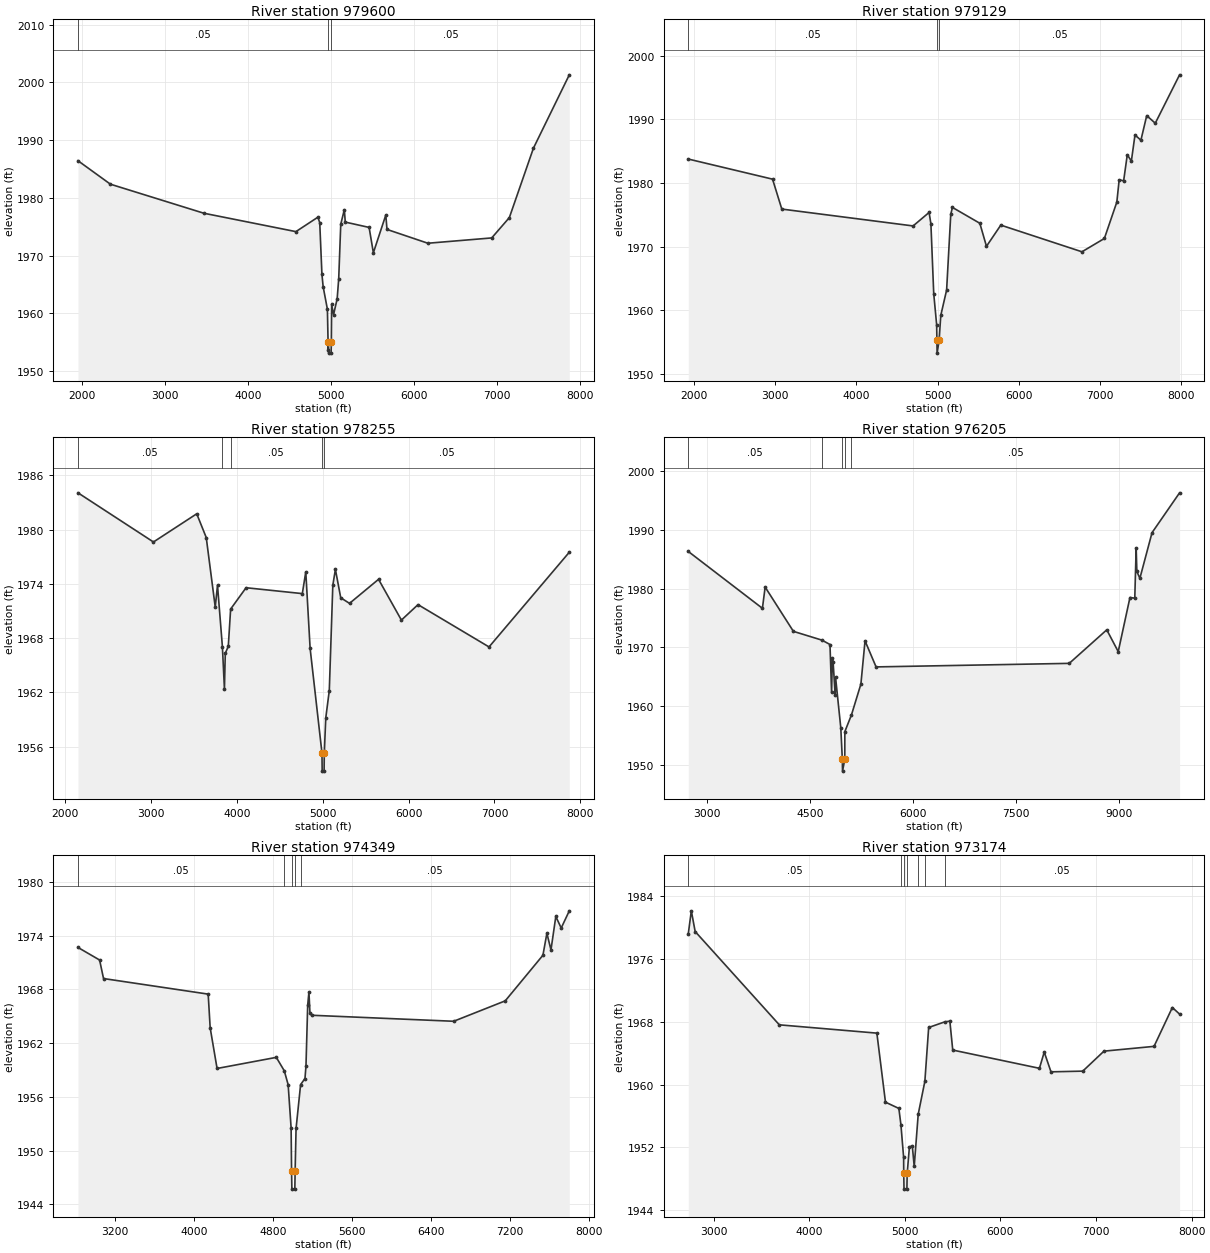
Type RM Length L Ch R = 1,979600,471,471,471
BEGIN DESCRIPTION:
Clear Fork Brazos Rv 258.0
END DESCRIPTION:
XS GIS Cut Line= 3
      1350957.25      6980479.15      1351643.59      6977417.04
      1352259.54      6974706.83
#Sta/Elev= 30
  1953.6 1986.44  2344.2 1982.38  3470.7 1977.35  4578.3 1974.17  4843.1 1976.67
  4865.2 1975.72  4891.6 1966.79  4906.2 1964.65  4957.5 1960.74  4967.7 1953.64
  4969.1 1955.14  4972.1 1953.14  5002.1 1953.14  5005.1 1955.14  5008.7 1961.57
  5031.9 1959.81  5075.3 1962.56  5093.8 1966.03  5118.5 1975.45  5161.5 1977.97
  5172.7 1975.82  5459.9 1974.90  5511.2 1970.51  5661.0 1977.04  5675.2 1974.55
  6167.5 1972.16  6936.6 1973.08  7149.0 1976.60  7439.1 1988.62  7871.0 2001.31
#Mann=3,-1,0
  1953.6    0.05       0  4969.1    0.05       0  5005.1    0.05       0
Bank Sta=4969.1,5005.1
Exp/Cntr=0.3,0.1

Type RM Length L Ch R = 1,979129,874,874,874
BEGIN DESCRIPTION:
Clear Fork Brazos Rv 257.0
END DESCRIPTION:
XS GIS Cut Line= 3
      1351274.02      6980549.56      1352065.95      6977610.62
      1352681.76      6974672.32
#Sta/Elev= 30
  1932.6 1983.75  2969.9 1980.59  3083.8 1975.89  4699.4 1973.24  4896.2 1975.36
  4918.6 1973.56  4953.3 1962.60  4989.3 1957.71  4992.5 1955.26  4994.7 1953.26
  5019.5 1955.26  5040.0 1959.18  5111.9 1963.17  5163.0 1975.08  5183.4 1976.15
  5520.6 1973.66  5602.3 1970.04  5778.6 1973.37  6777.3 1969.18  7053.1 1971.27
  7206.4 1976.99  7235.3 1980.49  7290.3 1980.33  7335.1 1984.43  7385.1 1983.42
  7429.9 1987.53  7502.7 1986.71  7574.2 1990.57  7679.5 1989.38  7978.5 1996.98
#Mann=3,-1,0
  1932.6    0.05       0  4992.5    0.03       0  5019.5    0.05       0
Bank Sta=4992.5,5019.5
Exp/Cntr=0.3,0.1

Type RM Length L Ch R = 1,978255,2050,2050,2050
BEGIN DESCRIPTION:
Clear Fork Brazos Rv 256.0
END DESCRIPTION:
XS GIS Cut Line= 3
      1352470.71      6980619.96      1352840.28      6977821.80
      1353473.83      6974988.43
#Sta/Elev= 30
  2146.4 1984.08  3025.9 1978.64  3530.3 1981.76  3641.2 1979.13  3746.0 1971.44
  3772.4 1973.85  3829.6 1967.03  3853.1 1962.39  3863.1 1966.32  3898.0 1967.10
  3925.4 1971.22  4105.2 1973.58  4760.9 1972.93  4801.2 1975.34  4851.7 1966.87
  4989.8 1955.29  4992.1 1953.29  5014.6 1953.29  5016.8 1955.29  5034.2 1959.18
  5075.2 1962.21  5116.2 1973.85  5146.4 1975.61  5208.4 1972.47  5310.9 1971.85
  5649.1 1974.51  5915.5 1970.00  6109.1 1971.71  6936.6 1967.03  7872.2 1977.51
#Mann=5,-1,0
  2146.4    0.05       0  3829.6    0.12       0  3925.4    0.05       0
  4989.8    0.05       0  5016.8    0.05       0
Bank Sta=4989.8,5016.8
Exp/Cntr=0.3,0.1

Type RM Length L Ch R = 1,976205,1856,1856,1856
BEGIN DESCRIPTION:
Clear Fork Brazos Rv 255.0
END DESCRIPTION:
XS GIS Cut Line= 3
      1353454.99      6981038.03      1354355.00      6978938.00
      1353849.98      6974088.79
#Sta/Elev= 30
  2722.6 1986.29  3803.3 1976.64  3843.2 1980.24  4254.9 1972.73  4671.1 1971.24
  4788.0 1970.50  4811.5 1962.39  4822.4 1968.19  4833.3 1967.57  4864.1 1961.96
  4869.6 1964.91  4945.7 1956.36  4967.9 1951.02  4970.9 1949.02  5003.9 1951.02
  5004.6 1955.72  5101.4 1958.57  5238.6 1963.79  5298.9 1971.12  5459.8 1966.70
  8274.9 1967.30  8821.8 1972.99  8988.8 1969.29  9159.7 1978.47  9230.1 1978.36
  9250.2 1986.91  9260.2 1982.89  9304.4 1981.73  9481.4 1989.47  9882.8 1996.23
#Mann=5,-1,0
  2722.6    0.05       0  4671.1    0.12       0  4967.9    0.07       0
  5003.9    0.12       0  5101.4    0.05       0
Bank Sta=4967.9,5003.9
Exp/Cntr=0.3,0.1

Type RM Length L Ch R = 1,974349,1175,1175,1175
BEGIN DESCRIPTION:
Clear Fork Brazos Rv 254.0
END DESCRIPTION:
XS GIS Cut Line= 3
      1355219.19      6979906.88      1355255.00      6977738.00
      1354992.27      6974941.89
#Sta/Elev= 30
  2823.0 1972.69  3041.9 1971.29  3081.9 1969.22  4142.1 1967.48  4162.1 1963.73
  4232.1 1959.18  4832.2 1960.42  4913.1 1958.92  4952.2 1957.37  4982.2 1952.55
  4986.9 1947.71  4989.9 1945.71  5019.9 1945.71  5022.9 1947.71  5032.4 1952.48
  5078.4 1957.38  5122.7 1958.06  5132.8 1959.45  5150.2 1966.25  5162.9 1967.71
  5173.0 1965.34  5193.1 1965.12  6629.4 1964.45  7151.6 1966.73  7533.3 1971.82
  7573.5 1974.27  7614.9 1972.42  7663.9 1976.15  7718.6 1974.86  7800.6 1976.78
#Mann=5,-1,0
  2823.0    0.05       0  4913.1    0.12       0  4986.9    0.07       0
  5022.9    0.12       0  5078.4    0.05       0
Bank Sta=4986.9,5022.9
Exp/Cntr=0.3,0.1

Type RM Length L Ch R = 1,973174,1439,1439,1439
BEGIN DESCRIPTION:
Clear Fork Brazos Rv 252.0
END DESCRIPTION:
XS GIS Cut Line= 3
      1356240.81      6980550.14      1356205.00      6978288.00
      1355862.46      6975432.80
#Sta/Elev= 30
  2735.9 1979.20  2768.0 1982.17  2808.1 1979.53  3688.2 1967.62  4708.3 1966.56
  4798.3 1957.75  4938.3 1956.95  4959.8 1954.88  4988.3 1950.70  4989.4 1948.65
  4992.4 1946.65  5022.4 1946.65  5025.4 1948.65  5048.7 1952.04  5078.9 1952.17
  5099.0 1949.55  5140.8 1956.21  5210.3 1960.41  5250.1 1967.28  5416.3 1967.99
  5471.7 1968.09  5501.9 1964.40  6408.4 1962.07  6458.7 1964.14  6529.2 1961.62
  6861.6 1961.71  7083.2 1964.26  7606.9 1964.87  7798.3 1969.83  7874.0 1968.99
#Mann=7,-1,0
  2735.9    0.05       0  4959.8    0.12       0  4989.4    0.07       0
  5025.4    0.12       0  5140.8    0.05       0  5210.3    0.12       0
  5416.3    0.05       0
Bank Sta=4989.4,5025.4
Exp/Cntr=0.3,0.1

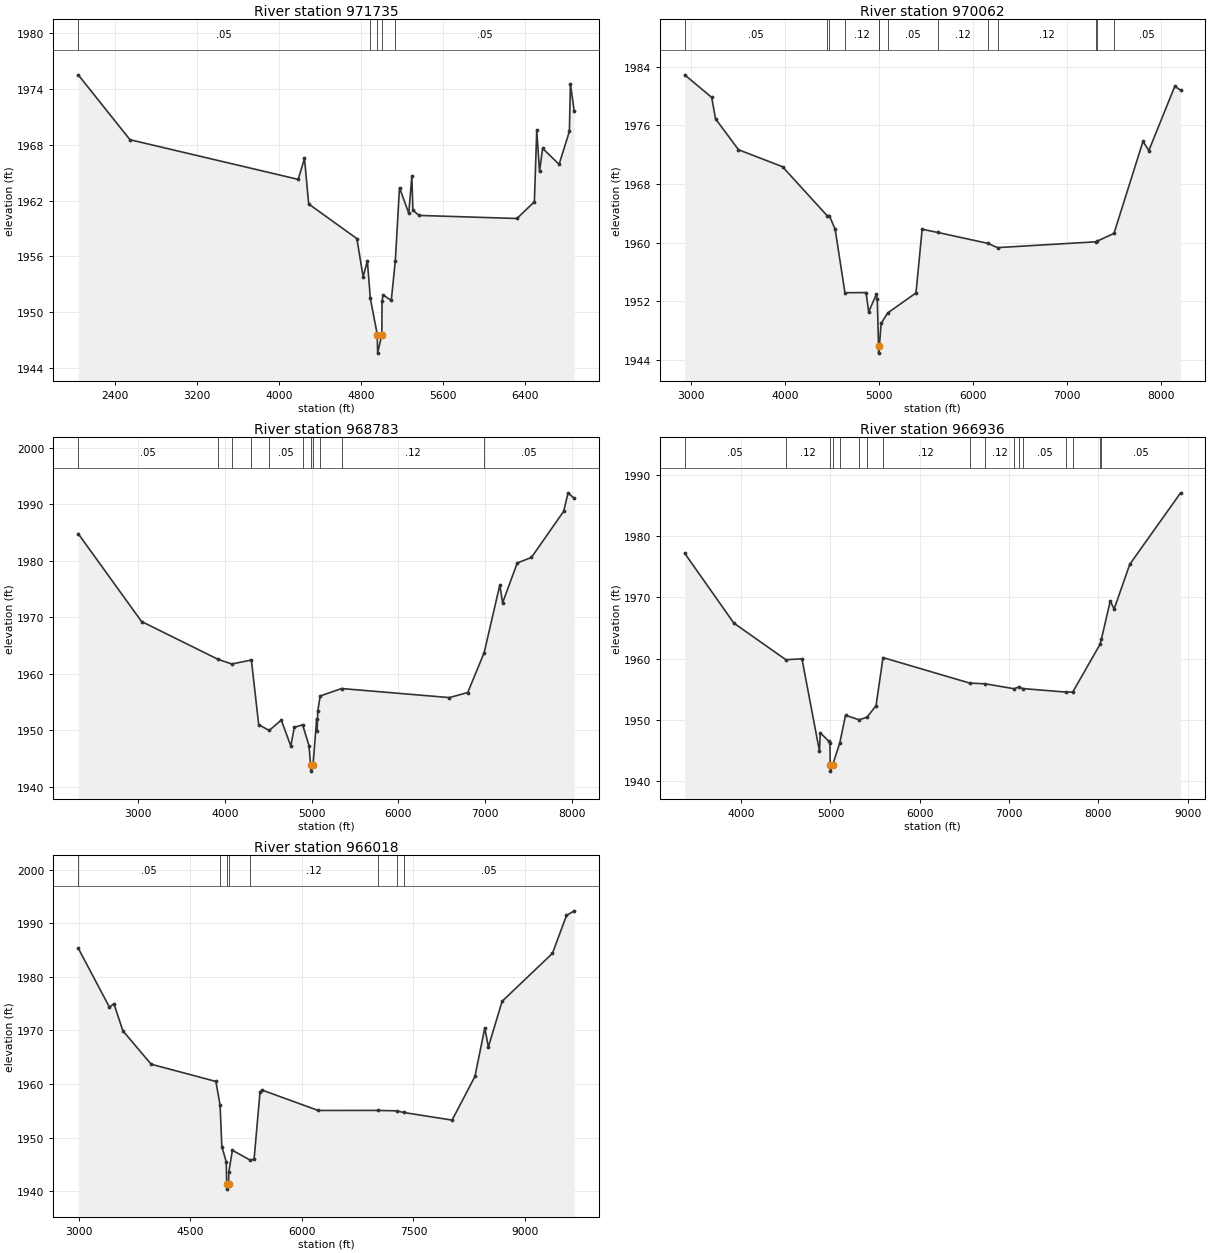
Type RM Length L Ch R = 1,971735,1673,1673,1673
BEGIN DESCRIPTION:
Clear Fork Brazos Rv 251.0
END DESCRIPTION:
XS GIS Cut Line= 3
      1356534.05      6980238.00      1357155.14      6977346.33
      1357347.44      6975471.68
#Sta/Elev= 30
  2040.9 1975.51  2546.3 1968.54  4188.8 1964.28  4250.2 1966.54  4291.1 1961.64
  4761.6 1957.92  4822.9 1953.81  4863.8 1955.53  4893.2 1951.50  4960.6 1947.62
  4964.3 1945.62  5005.6 1947.62  5006.9 1951.19  5016.9 1951.87  5097.4 1951.28
  5137.1 1955.56  5177.8 1963.39  5268.3 1960.64  5298.4 1964.64  5308.5 1960.97
  5368.8 1960.41  6324.4 1960.08  6494.7 1961.88  6517.9 1969.58  6544.9 1965.13
  6575.1 1967.61  6735.9 1965.90  6836.4 1969.43  6846.5 1974.56  6883.0 1971.64
#Mann=5,-1,0
  2040.9    0.05       0  4893.2    0.12       0  4960.6    0.07       0
  5005.6    0.12       0  5137.1    0.05       0
Bank Sta=4960.6,5005.6
Exp/Cntr=0.3,0.1

Type RM Length L Ch R = 1,970062,1279,1279,1279
BEGIN DESCRIPTION:
Clear Fork Brazos Rv 250.0
END DESCRIPTION:
XS GIS Cut Line= 3
      1357565.14      6980550.16      1357970.61      6978502.44
      1358255.50      6975321.05
#Sta/Elev= 30
  2932.3 1982.91  3219.9 1979.83  3260.7 1976.91  3505.4 1972.68  3974.3 1970.36
  4449.5 1963.67  4472.9 1963.69  4535.0 1961.80  4639.1 1953.15  4864.2 1953.17
  4891.8 1950.54  4973.3 1952.93  4983.5 1952.26  4996.8 1945.90  4997.5 1944.90
  5005.8 1945.90  5024.5 1948.95  5094.2 1950.39  5395.7 1953.12  5461.2 1961.82
  5625.3 1961.39  6160.8 1959.89  6263.9 1959.31  7316.9 1960.11  7320.7 1960.17
  7504.2 1961.25  7813.1 1973.82  7875.6 1972.57  8152.0 1981.35  8213.9 1980.81
#Mann=13,-1,0
  2932.3    0.05       0  4449.5    0.12       0  4472.9    0.05       0
  4639.1    0.12       0  4996.8    0.07       0  5005.8    0.12       0
  5094.2    0.05       0  5625.3    0.12       0  6160.8    0.05       0
  6263.9    0.12       0  7316.9    0.05       0  7320.7    0.12       0
  7504.2    0.05       0
Bank Sta=4996.8,5005.8
Exp/Cntr=0.3,0.1

Type RM Length L Ch R = 1,968783,1847,1847,1847
BEGIN DESCRIPTION:
Clear Fork Brazos Rv 249.0
END DESCRIPTION:
XS GIS Cut Line= 3
      1358855.00      6980638.03      1358855.00      6977938.00
      1358555.00      6974937.99
#Sta/Elev= 30
  2310.1 1984.79  3040.1 1969.26  3923.6 1962.56  4080.6 1961.75  4305.5 1962.46
  4390.1 1951.02  4510.8 1950.00  4650.1 1951.83  4760.1 1947.25  4800.1 1950.54
  4896.0 1951.00  4970.1 1947.29  4988.8 1943.81  4991.0 1942.81  5015.8 1943.81
  5057.9 1952.07  5062.9 1949.88  5070.4 1953.40  5098.7 1956.10  5344.9 1957.41
  6588.0 1955.81  6799.0 1956.71  6988.0 1963.75  7168.3 1975.70  7201.0 1972.58
  7369.3 1979.61  7532.6 1980.58  7904.5 1988.75  7954.7 1992.01  8025.1 1991.05
#Mann=11,-1,0
  2310.1    0.05       0  3923.6    0.12       0  4080.6    0.05       0
  4305.5    0.12       0  4510.8    0.05       0  4896.0    0.12       0
  4988.8    0.07       0  5015.8    0.12       0  5098.7    0.05       0
  5344.9    0.12       0  6988.0    0.05       0
Bank Sta=4988.8,5015.8
Exp/Cntr=0.3,0.1

Type RM Length L Ch R = 1,966936,918,918,918
BEGIN DESCRIPTION:
Clear Fork Brazos Rv 248.0
END DESCRIPTION:
XS GIS Cut Line= 3
      1359604.99      6980188.02      1360405.00      6978788.00
      1358805.01      6975188.01
#Sta/Elev= 30
  3367.6 1977.21  3918.3 1965.79  4500.9 1959.81  4680.6 1959.96  4876.4 1944.90
  4885.8 1947.87  4982.8 1946.47  4994.4 1946.23  4996.9 1942.61  4999.2 1941.61
  5023.9 1942.61  5104.1 1946.22  5168.2 1950.74  5321.0 1949.99  5410.3 1950.44
  5510.1 1952.32  5588.0 1960.16  6557.1 1956.00  6734.9 1955.87  7055.9 1955.07
  7106.9 1955.36  7153.3 1955.10  7638.1 1954.52  7711.9 1954.53  8016.2 1962.30
  8031.9 1963.12  8131.7 1969.39  8175.5 1968.10  8350.6 1975.41  8919.6 1987.08
#Mann=17,-1,0
  3367.6    0.05       0  4500.9    0.12       0  4996.9    0.03       0
  5023.9    0.05       0  5104.1    0.05       0  5321.0    0.12       0
  5410.3    0.05       0  5588.0    0.12       0  6557.1    0.05       0
  6734.9    0.12       0  7055.9    0.05       0  7106.9    0.12       0
  7153.3    0.05       0  7638.1    0.12       0  7711.9    0.05       0
  8016.2    0.12       0  8031.9    0.05       0
Bank Sta=4996.9,5023.9
Exp/Cntr=0.3,0.1

Type RM Length L Ch R = 1,966018,2786,2786,2786
BEGIN DESCRIPTION:
Clear Fork Brazos Rv 247.0
END DESCRIPTION:
XS GIS Cut Line= 3
      1361205.00      6980938.05      1361205.00      6978938.00
      1358805.01      6974938.01
#Sta/Elev= 30
  2994.5 1985.37  3414.5 1974.34  3474.5 1974.99  3594.5 1969.94  3974.5 1963.70
  4844.5 1960.48  4901.2 1956.04  4924.5 1948.33  4984.5 1945.44  4989.0 1941.37
  4991.2 1940.37  5016.0 1941.37  5017.9 1943.52  5066.5 1947.62  5303.2 1945.81
  5358.0 1945.95  5437.7 1958.50  5461.0 1958.89  6219.0 1955.06  7019.9 1955.07
  7273.7 1954.99  7368.0 1954.68  8018.9 1953.26  8326.0 1961.41  8458.1 1970.44
  8506.7 1966.93  8691.4 1975.45  9367.8 1984.40  9556.3 1991.47  9659.3 1992.34
#Mann=8,-1,0
  2994.5    0.05       0  4901.2    0.12       0  4989.0    0.07       0
  5016.0    0.12       0  5303.2    0.12       0  7019.9    0.05       0
  7273.7    0.12       0  7368.0    0.05       0
Bank Sta=4989,5016
Exp/Cntr=0.3,0.1