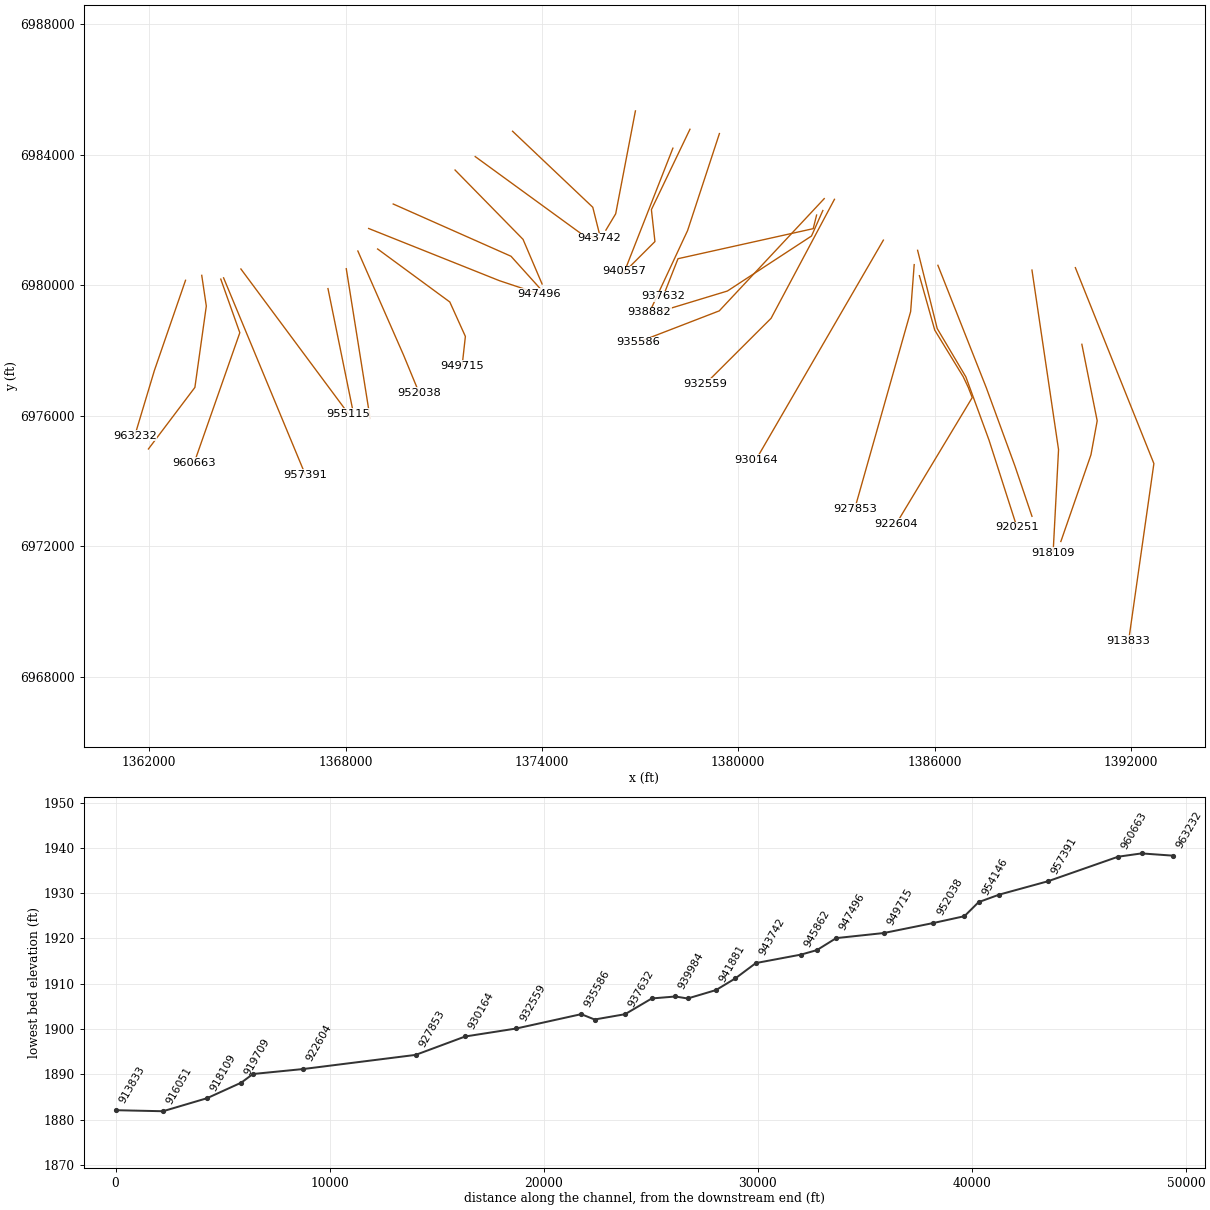
HEC-RAS study Clear Fork Brazos Rv.prj: Clear Fork Brazos Rv Base Level Engineering

--- Clear Fork Brazos Rv.g01 (geometry) --- (continued)

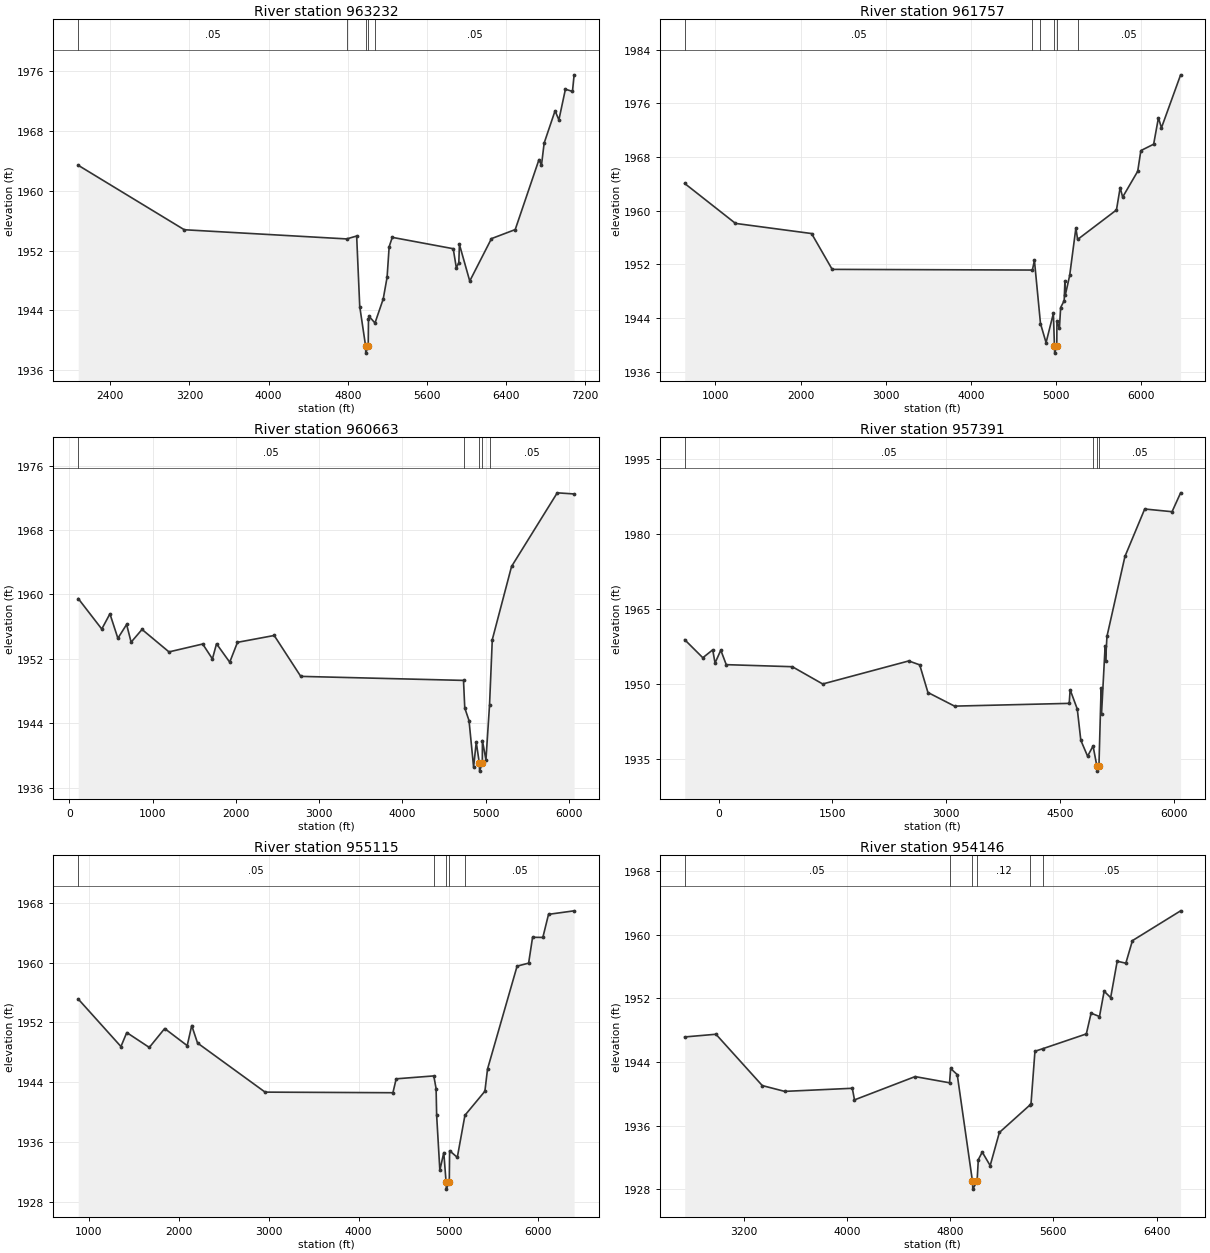
Type RM Length L Ch R = 1,963232,1475,1475,1475
BEGIN DESCRIPTION:
Clear Fork Brazos Rv 246.0
END DESCRIPTION:
XS GIS Cut Line= 3
      1363107.34      6980151.19      1362155.00      6977388.00
      1361554.99      6975387.96
#Sta/Elev= 30
  2076.5 1963.42  3148.2 1954.79  4789.5 1953.56  4890.0 1953.95  4921.2 1944.51
  4979.9 1939.27  4982.2 1938.27  5006.9 1939.27  5009.6 1942.87  5015.7 1943.20
  5075.2 1942.30  5158.4 1945.52  5197.6 1948.43  5218.4 1952.51  5249.8 1953.77
  5865.7 1952.25  5897.1 1949.70  5922.3 1950.37  5928.4 1952.82  6032.8 1947.92
  6252.0 1953.60  6492.2 1954.81  6732.3 1964.18  6757.5 1963.42  6784.5 1966.39
  6895.0 1970.72  6933.3 1969.49  6999.4 1973.60  7070.7 1973.31  7087.3 1975.53
#Mann=5,-1,0
  2076.5    0.05       0  4789.5    0.12       0  4979.9    0.07       0
  5006.9    0.12       0  5075.2    0.05       0
Bank Sta=4979.9,5006.9
Exp/Cntr=0.3,0.1

Type RM Length L Ch R = 1,961757,1094,1094,1094
BEGIN DESCRIPTION:
Mapping XS 850b9ee9
END DESCRIPTION:
XS GIS Cut Line= 4
      1363602.56      6980303.27      1363742.20      6979360.64
      1363393.07      6976870.12      1361973.22      6974984.75
#Sta/Elev= 30
   638.6 1964.05  1235.3 1958.10  2129.4 1956.59  2371.7 1951.25  4724.6 1951.15
  4748.5 1952.59  4819.7 1943.18  4885.2 1940.33  4971.2 1944.69  4984.1 1939.77
  4986.4 1938.77  5011.1 1939.77  5012.9 1943.56  5042.0 1942.44  5056.6 1945.56
  5098.3 1946.59  5106.6 1949.47  5112.8 1947.50  5162.8 1950.34  5235.7 1957.41
  5256.2 1955.71  5712.5 1960.10  5756.2 1963.44  5785.3 1962.02  5962.3 1965.87
  5999.3 1968.95  6149.6 1969.90  6205.9 1973.84  6241.3 1972.34  6466.6 1980.24
#Mann=6,-1,0
   638.6    0.05       0  4724.6    0.12       0  4819.7    0.05       0
  4984.1    0.07       0  5011.1    0.05       0  5256.2    0.05       0
Bank Sta=4984.1,5011.1
Exp/Cntr=0.3,0.1

Type RM Length L Ch R = 1,960663,3272,3272,3272
BEGIN DESCRIPTION:
Mapping XS 22c80ff6
END DESCRIPTION:
XS GIS Cut Line= 3
      1364184.46      6980186.89      1364766.29      6978546.00
      1363374.25      6974568.76
#Sta/Elev= 30
   107.5 1959.48   390.4 1955.69   488.4 1957.58   583.8 1954.54   688.6 1956.26
   742.9 1954.06   873.8 1955.64  1197.6 1952.85  1602.3 1953.83  1719.0 1951.98
  1768.3 1953.86  1926.9 1951.57  2020.0 1954.04  2460.9 1954.89  2779.8 1949.81
  4734.2 1949.31  4749.3 1945.88  4800.4 1944.32  4855.3 1938.54  4887.1 1941.64
  4924.1 1939.04  4927.1 1938.04  4960.1 1939.04  4961.2 1941.84  5003.6 1939.44
  5046.9 1946.29  5079.7 1954.37  5310.9 1963.46  5859.9 1972.61  6062.3 1972.47
#Mann=5,-1,0
   107.5    0.05       0  4734.2    0.12       0  4924.1    0.07       0
  4960.1    0.12       0  5046.9    0.05       0
Bank Sta=4924.1,4960.1
Exp/Cntr=0.3,0.1

Type RM Length L Ch R = 1,957391,2276,2276,2276
BEGIN DESCRIPTION:
Mapping XS 9d5f8b6f
END DESCRIPTION:
XS GIS Cut Line= 3
      1364270.17      6980226.90      1365207.59      6977964.60
      1366770.06      6974193.83
#Sta/Elev= 30
  -446.1 1958.87  -207.6 1955.27   -77.3 1956.85   -46.8 1954.22    29.0 1956.78
   100.7 1953.89   970.7 1953.48  1371.2 1950.03  2503.9 1954.63  2648.5 1953.85
  2756.8 1948.33  3107.4 1945.61  4617.3 1946.16  4629.4 1948.88  4723.6 1945.02
  4770.1 1938.79  4859.3 1935.61  4931.3 1937.65  4981.7 1933.63  4984.0 1932.63
  5008.7 1933.63  5037.3 1949.20  5042.7 1944.00  5090.5 1957.67  5095.9 1954.59
  5114.4 1959.54  5351.0 1975.49  5611.5 1984.97  5971.6 1984.43  6084.4 1988.20
#Mann=4,-1,0
  -446.1    0.05       0  4931.3    0.12       0  4981.7    0.05       0
  5008.7    0.05       0
Bank Sta=4981.7,5008.7
Exp/Cntr=0.3,0.1

Type RM Length L Ch R = 1,955115,969,969,969
BEGIN DESCRIPTION:
Mapping XS 39cd8afb
END DESCRIPTION:
XS GIS Cut Line= 3
      1364799.44      6980497.92      1365874.26      6979047.93
      1368082.59      6976068.76
#Sta/Elev= 30
   883.1 1955.12  1358.2 1948.76  1422.9 1950.63  1673.4 1948.64  1844.5 1951.17
  2094.9 1948.88  2145.0 1951.57  2209.7 1949.23  2960.9 1942.66  4382.0 1942.58
  4418.2 1944.44  4836.5 1944.83  4862.0 1943.13  4868.2 1939.54  4903.7 1932.21
  4947.5 1934.57  4972.7 1930.68  4975.7 1929.68  5008.7 1930.68  5012.2 1934.82
  5097.8 1933.93  5182.6 1939.56  5404.5 1942.78  5433.8 1945.75  5762.5 1959.52
  5890.7 1959.92  5934.6 1963.38  6048.8 1963.36  6111.9 1966.45  6396.4 1966.92
#Mann=5,-1,0
   883.1    0.05       0  4836.5    0.12       0  4972.7    0.07       0
  5008.7    0.12       0  5182.6    0.05       0
Bank Sta=4972.7,5008.7
Exp/Cntr=0.3,0.1

Type RM Length L Ch R = 1,954146,662,662,662
BEGIN DESCRIPTION:
Mapping XS 3d60ee60
END DESCRIPTION:
XS GIS Cut Line= 2
      1367461.02      6979896.90      1368228.25      6976132.09
#Sta/Elev= 30
  2743.8 1947.16  2985.8 1947.50  3344.8 1941.04  3518.3 1940.31  4042.3 1940.70
  4059.2 1939.24  4528.7 1942.17  4795.8 1941.39  4804.2 1943.19  4855.2 1942.42
  4973.1 1929.01  4976.1 1928.01  5009.1 1929.01  5018.5 1931.72  5049.1 1932.67
  5110.4 1930.97  5181.8 1935.14  5417.5 1938.58  5426.7 1938.72  5457.4 1945.36
  5521.5 1945.70  5855.4 1947.54  5892.4 1950.15  5957.4 1949.73  5993.5 1952.91
  6044.0 1952.11  6094.6 1956.69  6161.5 1956.44  6212.6 1959.28  6586.0 1963.03
#Mann=6,-1,0
  2743.8    0.05       0  4795.8    0.12       0  4973.1    0.05       0
  5009.1    0.12       0  5417.5    0.12       0  5521.5    0.05       0
Bank Sta=4973.1,5009.1
Exp/Cntr=0.3,0.1

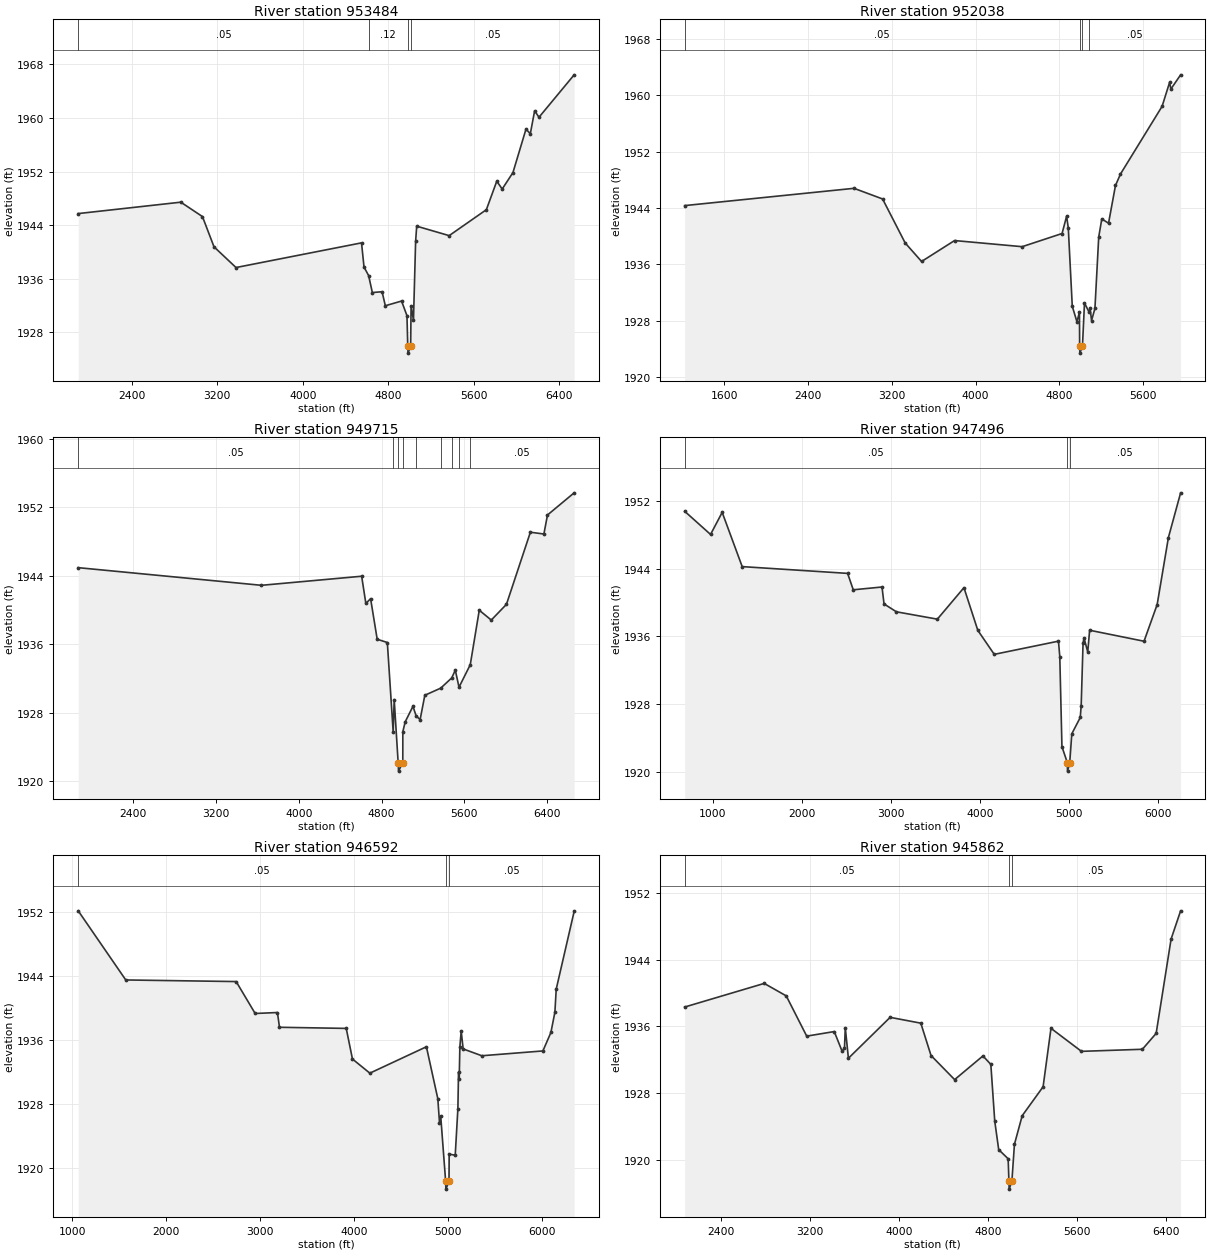
Type RM Length L Ch R = 1,953484,1446,1446,1446
BEGIN DESCRIPTION:
Mapping XS 7f84c7f1
END DESCRIPTION:
XS GIS Cut Line= 2
      1368020.08      6980506.30      1368749.25      6975922.94
#Sta/Elev= 30
  1898.0 1945.73  2858.2 1947.43  3060.7 1945.28  3168.7 1940.77  3374.6 1937.68
  4549.2 1941.36  4572.6 1937.75  4615.6 1936.48  4650.5 1933.95  4741.6 1934.07
  4772.0 1931.98  4923.9 1932.68  4974.5 1930.50  4981.9 1925.91  4984.1 1924.91
  5008.9 1925.91  5013.1 1931.98  5035.3 1929.82  5055.5 1941.60  5065.6 1943.85
  5369.4 1942.44  5717.5 1946.31  5814.9 1950.56  5865.6 1949.39  5966.3 1951.85
  6088.3 1958.33  6128.8 1957.64  6169.3 1961.07  6209.9 1960.10  6539.0 1966.43
#Mann=4,-1,0
  1898.0    0.05       0  4615.6    0.12       0  4981.9    0.05       0
  5008.9    0.05       0
Bank Sta=4981.9,5008.9
Exp/Cntr=0.3,0.1

Type RM Length L Ch R = 1,952038,2323,2323,2323
BEGIN DESCRIPTION:
Clear Fork Brazos Rv 239.0
END DESCRIPTION:
XS GIS Cut Line= 3
      1368374.24      6981047.96      1369769.14      6977865.43
      1370248.24      6976701.91
#Sta/Elev= 30
  1223.2 1944.34  2839.1 1946.79  3112.0 1945.28  3327.5 1939.04  3484.1 1936.41
  3798.9 1939.38  4444.1 1938.51  4825.0 1940.38  4868.3 1942.84  4884.3 1941.16
  4922.3 1930.06  4966.9 1927.85  4990.9 1929.25  4992.6 1924.41  4994.8 1923.41
  5019.6 1924.41  5038.8 1930.52  5083.4 1929.21  5092.1 1929.81  5106.2 1928.03
  5138.6 1929.75  5174.7 1939.88  5204.1 1942.45  5268.4 1941.84  5334.6 1947.19
  5382.5 1948.82  5779.6 1958.42  5851.4 1961.83  5863.2 1960.87  5956.3 1962.89
#Mann=4,-1,0
  1223.2    0.05       0  4992.6    0.05       0  5019.6    0.05       0
  5083.4    0.05       0
Bank Sta=4992.6,5019.6
Exp/Cntr=0.3,0.1

Type RM Length L Ch R = 1,949715,2219,2219,2219
BEGIN DESCRIPTION:
Clear Fork Brazos Rv 238.0
END DESCRIPTION:
XS GIS Cut Line= 4
      1368978.41      6981110.44      1371185.03      6979486.86
      1371660.78      6978431.95      1371561.48      6977537.23
#Sta/Elev= 30
  1866.1 1944.95  3638.5 1942.89  4607.8 1943.95  4648.3 1940.77  4694.2 1941.33
  4758.0 1936.59  4856.1 1936.21  4912.5 1925.80  4922.5 1929.55  4960.7 1922.19
  4964.5 1921.19  5005.7 1922.19  5005.9 1925.79  5029.0 1926.95  5103.9 1928.76
  5135.1 1927.63  5173.3 1927.21  5218.7 1930.05  5372.4 1930.88  5478.5 1932.07
  5513.6 1932.98  5549.4 1930.99  5658.3 1933.62  5745.3 1939.98  5861.5 1938.83
  6008.3 1940.67  6239.7 1949.09  6370.5 1948.88  6405.1 1951.10  6663.1 1953.69
#Mann=9,-1,0
  1866.1    0.05       0  4912.5    0.12       0  4960.7    0.07       0
  5005.7    0.12       0  5135.1    0.05       0  5372.4    0.12       0
  5478.5    0.05       0  5549.4    0.12       0  5658.3    0.05       0
Bank Sta=4960.7,5005.7
Exp/Cntr=0.3,0.1

Type RM Length L Ch R = 1,947496,904,904,904
BEGIN DESCRIPTION:
Clear Fork Brazos Rv 236.0
END DESCRIPTION:
XS GIS Cut Line= 3
      1368704.97      6981738.01      1372705.00      6980138.00
      1373905.02      6979737.99
#Sta/Elev= 30
   683.1 1950.78   973.9 1948.04  1104.5 1950.65  1329.4 1944.24  2514.1 1943.44
  2577.4 1941.50  2900.5 1941.83  2923.4 1939.83  3062.0 1938.90  3522.5 1938.03
  3821.3 1941.75  3977.5 1936.70  4162.0 1933.87  4883.6 1935.43  4898.4 1933.60
  4922.6 1922.96  4983.1 1921.07  4985.3 1920.07  5010.1 1921.07  5033.4 1924.48
  5128.3 1926.41  5138.8 1927.81  5159.9 1935.21  5170.5 1935.81  5212.6 1934.16
  5233.7 1936.72  5845.1 1935.42  5992.7 1939.76  6119.1 1947.68  6256.2 1952.96
#Mann=3,-1,0
   683.1    0.05       0  4983.1    0.05       0  5010.1    0.05       0
Bank Sta=4983.1,5010.1
Exp/Cntr=0.3,0.1

Type RM Length L Ch R = 1,946592,730,730,730
BEGIN DESCRIPTION:
Clear Fork Brazos Rv 235.0
END DESCRIPTION:
XS GIS Cut Line= 3
      1369455.03      6982487.99      1373055.00      6980888.00
      1373955.02      6979887.98
#Sta/Elev= 30
  1061.3 1952.12  1568.1 1943.50  2744.5 1943.30  2946.9 1939.32  3184.2 1939.44
  3206.1 1937.60  3917.4 1937.46  3983.8 1933.64  4169.1 1931.88  4771.7 1935.17
  4893.4 1928.69  4911.2 1925.72  4924.2 1926.53  4976.6 1918.42  4979.6 1917.42
  5012.6 1918.42  5014.6 1921.78  5078.9 1921.65  5107.3 1927.47  5114.0 1932.01
  5121.5 1931.19  5128.3 1935.16  5142.5 1937.12  5163.4 1934.90  5362.2 1934.05
  6013.2 1934.65  6098.4 1936.95  6141.0 1939.48  6155.2 1942.36  6346.2 1952.05
#Mann=3,-1,0
  1061.3    0.05       0  4976.6    0.05       0  5012.6    0.05       0
Bank Sta=4976.6,5012.6
Exp/Cntr=0.3,0.1

Type RM Length L Ch R = 1,945862,2120,2120,2120
BEGIN DESCRIPTION:
Clear Fork Brazos Rv 234.0
END DESCRIPTION:
XS GIS Cut Line= 3
      1371344.92      6983528.98      1373423.06      6981405.17
      1374005.01      6980037.97
#Sta/Elev= 30
  2072.7 1938.34  2787.6 1941.18  2985.6 1939.68  3169.5 1934.84  3417.1 1935.39
  3487.7 1933.02  3509.0 1933.40  3516.0 1935.85  3544.3 1932.18  3919.2 1937.10
  4194.9 1936.40  4286.8 1932.51  4498.9 1929.61  4753.5 1932.46  4824.3 1931.44
  4859.5 1924.61  4895.0 1921.19  4979.9 1920.09  4986.8 1917.44  4989.1 1916.44
  5013.8 1917.44  5036.4 1921.83  5106.2 1925.27  5294.0 1928.75  5364.9 1935.78
  5638.8 1933.01  6186.4 1933.26  6310.1 1935.17  6444.5 1946.52  6530.0 1949.91
#Mann=3,-1,0
  2072.7    0.05       0  4986.8   0.035       0  5013.8    0.05       0
Bank Sta=4986.8,5013.8
Exp/Cntr=0.3,0.1

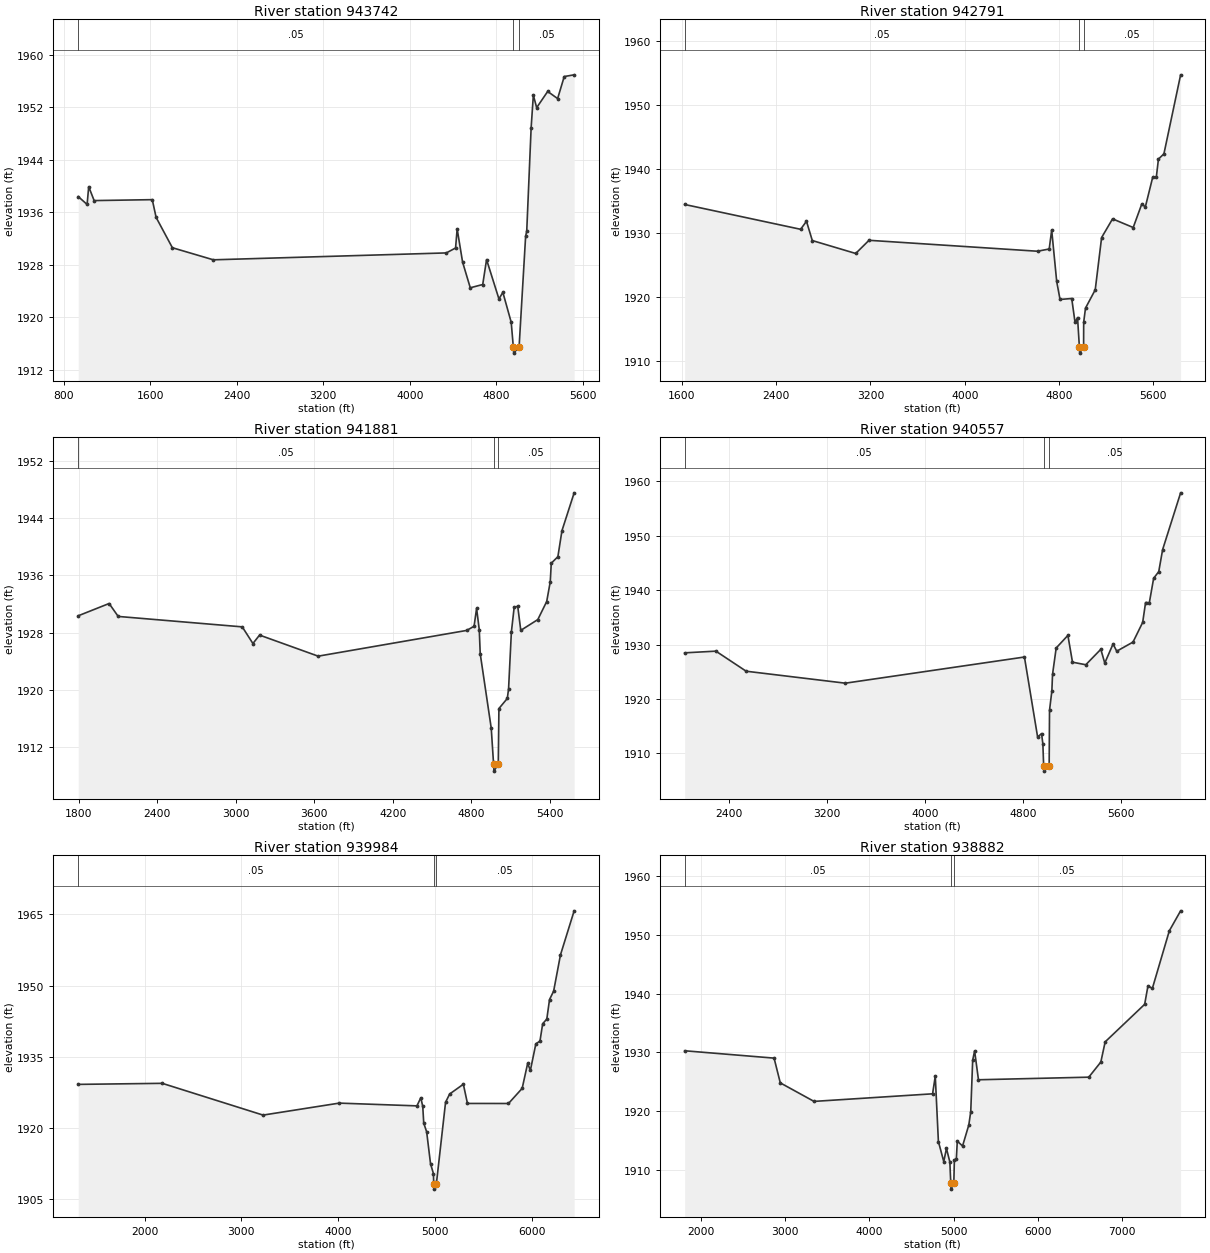
Type RM Length L Ch R = 1,943742,951,951,951
BEGIN DESCRIPTION:
Clear Fork Brazos Rv 233.0
END DESCRIPTION:
XS GIS Cut Line= 3
      1371961.48      6983940.09      1375255.00      6981538.00
      1375754.97      6981438.01
#Sta/Elev= 30
   933.1 1938.40  1015.5 1937.20  1030.1 1939.91  1080.3 1937.79  1618.0 1937.93
  1653.5 1935.23  1803.9 1930.61  2182.7 1928.77  4337.1 1929.82  4422.8 1930.57
  4437.5 1933.47  4487.7 1928.42  4558.8 1924.51  4673.9 1925.01  4709.4 1928.80
  4823.9 1922.81  4860.1 1923.82  4937.3 1919.26  4956.5 1915.56  4961.0 1914.56
  5010.5 1915.56  5070.7 1932.37  5080.9 1933.13  5121.7 1948.91  5142.1 1953.84
  5172.7 1951.94  5274.7 1954.41  5366.5 1953.32  5427.7 1956.68  5519.4 1956.94
#Mann=3,-1,0
   933.1    0.05       0  4956.5    0.05       0  5010.5    0.05       0
Bank Sta=4956.5,5010.5
Exp/Cntr=0.3,0.1

Type RM Length L Ch R = 1,942791,910,910,910
BEGIN DESCRIPTION:
Clear Fork Brazos Rv 232.0
END DESCRIPTION:
XS GIS Cut Line= 3
      1373103.36      6984716.52      1375555.00      6982388.00
      1375755.00      6981588.02
#Sta/Elev= 30
  1624.9 1934.44  2608.1 1930.56  2657.8 1931.82  2707.2 1928.80  3075.2 1926.78
  3188.1 1928.84  4617.2 1927.13  4716.3 1927.48  4737.3 1930.45  4779.8 1922.40
  4808.1 1919.59  4907.2 1919.74  4935.5 1915.99  4956.6 1916.76  4972.0 1912.20
  4975.0 1911.20  5008.0 1912.20  5008.7 1916.04  5024.1 1918.24  5106.6 1921.10
  5160.7 1929.27  5253.5 1932.19  5428.7 1930.84  5500.9 1934.49  5531.8 1934.07
  5593.6 1938.67  5624.6 1938.70  5642.6 1941.54  5689.0 1942.35  5830.7 1954.71
#Mann=3,-1,0
  1624.9    0.05       0  4972.0    0.05       0  5008.0    0.05       0
Bank Sta=4972,5008
Exp/Cntr=0.3,0.1

Type RM Length L Ch R = 1,941881,1324,1324,1324
BEGIN DESCRIPTION:
Clear Fork Brazos Rv 231.0
END DESCRIPTION:
XS GIS Cut Line= 3
      1376858.09      6985340.13      1376255.00      6982188.00
      1375955.00      6981688.00
#Sta/Elev= 30
  1795.2 1930.34  2031.5 1932.06  2101.0 1930.25  3049.7 1928.79  3131.1 1926.46
  3182.0 1927.64  3630.0 1924.69  4765.1 1928.29  4822.3 1928.87  4841.6 1931.38
  4862.0 1928.39  4869.3 1925.03  4953.6 1914.61  4971.4 1909.60  4974.4 1908.60
  5007.4 1909.60  5012.3 1917.36  5076.4 1918.77  5086.1 1920.11  5107.5 1928.06
  5128.9 1931.52  5156.1 1931.67  5179.4 1928.30  5309.7 1929.81  5377.7 1932.34
  5404.9 1935.11  5412.7 1937.70  5463.2 1938.61  5494.3 1942.25  5587.6 1947.55
#Mann=3,-1,0
  1795.2    0.05       0  4971.4    0.05       0  5007.4    0.05       0
Bank Sta=4971.4,5007.4
Exp/Cntr=0.3,0.1

Type RM Length L Ch R = 1,940557,573,573,573
BEGIN DESCRIPTION:
Mapping XS 64fdcfc3
END DESCRIPTION:
XS GIS Cut Line= 2
      1378003.57      6984198.19      1376528.30      6980431.92
#Sta/Elev= 30
  2039.7 1928.49  2294.3 1928.80  2541.2 1925.11  3350.2 1922.91  4810.8 1927.72
  4918.2 1913.02  4950.4 1913.64  4961.1 1911.74  4967.5 1907.74  4971.3 1906.74
  5012.5 1907.74  5015.4 1917.93  5034.5 1921.49  5039.9 1924.52  5069.7 1929.38
  5165.2 1931.70  5202.7 1926.77  5311.2 1926.30  5433.7 1929.14  5465.9 1926.61
  5533.6 1930.12  5563.5 1928.79  5696.4 1930.47  5775.2 1934.09  5798.8 1937.74
  5829.4 1937.70  5864.6 1942.20  5906.2 1943.42  5938.0 1947.48  6084.6 1957.91
#Mann=3,-1,0
  2039.7    0.05       0  4967.5    0.05       0  5012.5    0.05       0
Bank Sta=4967.5,5012.5
Exp/Cntr=0.3,0.1

Type RM Length L Ch R = 1,939984,1102,1102,1102
BEGIN DESCRIPTION:
Clear Fork Brazos Rv 230.0
END DESCRIPTION:
XS GIS Cut Line= 4
      1378524.75      6984777.60      1377346.37      6982315.64
      1377455.00      6981338.00      1376455.00      6980338.00
#Sta/Elev= 30
  1313.1 1929.21  2182.0 1929.43  3224.3 1922.75  4011.6 1925.27  4814.9 1924.69
  4855.1 1926.40  4875.3 1924.56  4885.3 1921.07  4915.5 1919.23  4955.8 1912.49
  4985.9 1910.44  4988.3 1908.18  4990.6 1907.18  5015.3 1908.18  5111.0 1925.45
  5153.5 1927.19  5294.9 1929.24  5337.3 1925.20  5761.6 1925.19  5903.0 1928.37
  5959.6 1933.62  5987.9 1932.16  6044.4 1937.74  6086.9 1938.31  6115.1 1941.97
  6157.6 1942.94  6185.8 1947.05  6228.3 1948.82  6299.0 1956.45  6440.4 1965.71
#Mann=3,-1,0
  1313.1    0.05       0  4988.3    0.05       0  5015.3    0.05       0
Bank Sta=4988.3,5015.3
Exp/Cntr=0.3,0.1

Type RM Length L Ch R = 1,938882,1250,1250,1250
BEGIN DESCRIPTION:
Mapping XS 4ea56388
END DESCRIPTION:
XS GIS Cut Line= 3
      1379425.36      6984645.52      1378453.16      6981676.81
      1377289.96      6979176.82
#Sta/Elev= 30
  1810.5 1930.28  2870.7 1929.03  2944.3 1924.82  3344.2 1921.67  4750.3 1922.96
  4782.2 1925.96  4819.3 1914.84  4883.0 1911.43  4914.8 1913.67  4955.1 1911.36
  4966.0 1907.75  4969.0 1906.75  5002.0 1907.75  5008.8 1911.71  5031.7 1911.80
  5043.3 1914.90  5105.9 1914.09  5180.0 1917.67  5202.9 1919.93  5225.8 1928.68
  5248.7 1930.26  5294.4 1925.35  6602.6 1925.79  6745.4 1928.36  6797.0 1931.80
  7265.3 1938.18  7304.4 1941.31  7356.9 1940.90  7558.0 1950.69  7691.7 1954.08
#Mann=3,-1,0
  1810.5    0.05       0  4966.0    0.05       0  5002.0    0.05       0
Bank Sta=4966,5002
Exp/Cntr=0.3,0.1

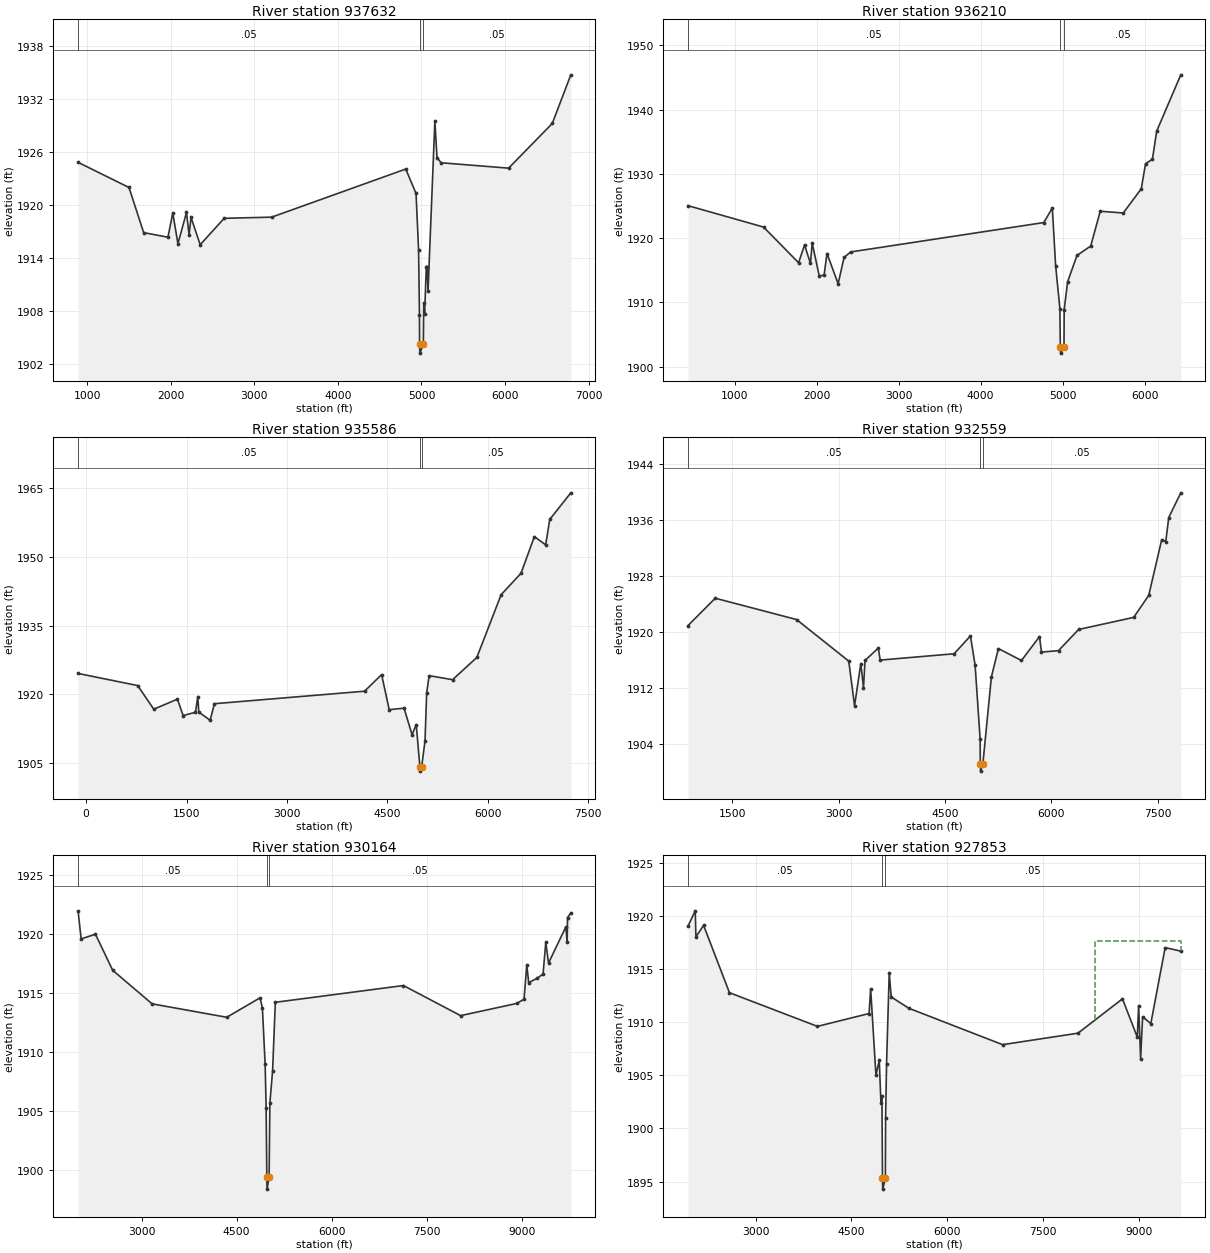
Type RM Length L Ch R = 1,937632,1422,1422,1422
BEGIN DESCRIPTION:
Mapping XS 4fdb89c1
END DESCRIPTION:
XS GIS Cut Line= 4
      1382395.93      6982149.58      1382291.75      6981732.88
      1378159.81      6980812.74      1377708.42      6979666.92
#Sta/Elev= 30
   892.4 1924.88  1501.6 1922.03  1677.2 1916.92  1967.3 1916.40  2025.5 1919.13
  2087.0 1915.66  2189.4 1919.21  2220.1 1916.66  2243.6 1918.64  2353.3 1915.55
  2640.2 1918.54  3208.2 1918.67  4812.1 1924.12  4935.1 1921.35  4965.8 1914.94
  4976.0 1907.64  4977.5 1904.27  4981.3 1903.27  5022.5 1904.27  5027.3 1909.00
  5037.5 1907.65  5058.0 1913.08  5068.2 1913.08  5078.5 1910.26  5160.4 1929.54
  5186.0 1925.42  5234.6 1924.83  6042.1 1924.22  6564.6 1929.28  6786.6 1934.79
#Mann=3,-1,0
   892.4    0.05       0  4977.5    0.05       0  5022.5    0.05       0
Bank Sta=4977.5,5022.5
Exp/Cntr=0.3,0.1

Type RM Length L Ch R = 1,936210,624,624,624
BEGIN DESCRIPTION:
Mapping XS 8a45e9e4
END DESCRIPTION:
XS GIS Cut Line= 4
      1382586.90      6982288.46      1382239.67      6981507.19
      1379670.22      6979823.16      1377673.73      6979215.53
#Sta/Elev= 30
   428.6 1925.06  1350.4 1921.73  1778.6 1916.17  1850.9 1918.95  1922.8 1916.07
  1944.3 1919.21  2030.4 1914.13  2089.1 1914.24  2125.2 1917.61  2260.8 1912.90
  2333.2 1916.99  2413.0 1917.85  4771.2 1922.43  4875.0 1924.70  4915.1 1915.74
  4967.4 1909.02  4972.5 1903.10  4976.3 1902.10  5017.5 1903.10  5019.7 1908.88
  5061.5 1913.21  5175.9 1917.31  5343.7 1918.78  5459.6 1924.19  5740.9 1923.92
  5960.4 1927.69  6012.7 1931.59  6096.3 1932.28  6148.6 1936.66  6442.6 1945.43
#Mann=3,-1,0
   428.6    0.05       0  4972.5    0.05       0  5017.5    0.05       0
Bank Sta=4972.5,5017.5
Exp/Cntr=0.3,0.1

Type RM Length L Ch R = 1,935586,3027,3027,3027
BEGIN DESCRIPTION:
Mapping XS 2ff0a6de
END DESCRIPTION:
XS GIS Cut Line= 3
      1382628.89      6982652.56      1379420.58      6979215.09
      1376941.42      6978256.76
#Sta/Elev= 30
  -120.5 1924.59   770.0 1921.95  1010.3 1916.79  1364.0 1918.98  1449.0 1915.41
  1633.2 1916.12  1668.4 1919.55  1682.5 1916.17  1852.5 1914.38  1916.0 1917.99
  4158.9 1920.72  4413.4 1924.34  4526.8 1916.69  4748.4 1917.02  4868.2 1911.22
  4930.6 1913.44  4985.0 1904.28  4987.3 1903.28  5012.0 1904.28  5061.8 1909.91
  5086.3 1920.36  5123.6 1924.11  5473.5 1923.23  5836.0 1928.09  6198.5 1941.78
  6495.8 1946.45  6694.7 1954.44  6863.7 1952.65  6924.8 1958.20  7239.5 1964.00
#Mann=3,-1,0
  -120.5    0.05       0  4985.0    0.05       0  5012.0    0.05       0
Bank Sta=4985,5012
Exp/Cntr=0.3,0.1

Type RM Length L Ch R = 1,932559,2395,2395,2395
BEGIN DESCRIPTION:
Clear Fork Brazos Rv 228.0
END DESCRIPTION:
XS GIS Cut Line= 3
      1382941.41      6982631.74      1381005.00      6978988.00
      1379005.03      6976988.03
#Sta/Elev= 30
   873.8 1920.92  1258.9 1924.83  2406.1 1921.78  3142.9 1915.84  3224.3 1909.47
  3312.8 1915.48  3350.5 1912.06  3372.5 1915.94  3559.0 1917.70  3586.6 1915.99
  4629.6 1916.89  4860.1 1919.44  4926.0 1915.23  4997.3 1904.66  4999.0 1901.12
  5002.0 1900.12  5035.0 1901.12  5155.7 1913.58  5254.7 1917.63  5579.9 1915.93
  5834.5 1919.34  5862.8 1917.13  6103.2 1917.34  6386.1 1920.36  7163.9 1922.09
  7376.0 1925.23  7559.8 1933.21  7616.4 1932.91  7658.8 1936.36  7828.5 1939.89
#Mann=3,-1,0
   873.8    0.05       0  4999.0    0.05       0  5035.0    0.05       0
Bank Sta=4999,5035
Exp/Cntr=0.3,0.1

Type RM Length L Ch R = 1,930164,2311,2311,2311
BEGIN DESCRIPTION:
Mapping XS 2f1831d1
END DESCRIPTION:
XS GIS Cut Line= 2
      1384436.77      6981381.29      1380541.17      6974652.52
#Sta/Elev= 30
  1998.4 1921.93  2047.2 1919.55  2272.6 1919.95  2545.2 1916.89  3166.5 1914.05
  4344.6 1912.91  4869.8 1914.56  4907.1 1913.70  4950.2 1908.94  4965.9 1905.25
  4977.0 1899.35  4980.0 1898.35  5013.0 1899.35  5024.8 1905.62  5067.8 1908.36
  5110.9 1914.18  7132.6 1915.60  8033.8 1913.05  8917.7 1914.08  9035.4 1914.44
  9078.5 1917.36  9108.5 1915.84  9239.2 1916.21  9335.3 1916.57  9378.4 1919.28
  9421.4 1917.50  9694.0 1920.56  9715.6 1919.28  9721.3 1921.36  9773.5 1921.75
#Mann=3,-1,0
  1998.4    0.05       0  4977.0    0.05       0  5013.0    0.05       0
Bank Sta=4977,5013
Exp/Cntr=0.3,0.1

Type RM Length L Ch R = 1,927853,5249,5249,5249
BEGIN DESCRIPTION:
Mapping XS 5a25643e
END DESCRIPTION:
XS GIS Cut Line= 3
      1385378.91      6980631.73      1385270.09      6979193.76
      1383561.87      6973152.50
#Sta/Elev= 30
  1940.4 1919.03  2054.0 1920.47  2064.5 1918.02  2184.8 1919.10  2589.8 1912.77
  3968.0 1909.60  4777.6 1910.81  4801.8 1913.13  4884.7 1905.01  4936.9 1906.40
  4963.0 1902.40  4978.5 1903.08  4987.5 1895.29  4991.3 1894.29  5032.5 1895.29
  5036.1 1901.02  5051.2 1906.08  5092.8 1914.65  5123.9 1912.37  5401.8 1911.30
  6869.5 1907.88  8049.8 1908.96  8747.1 1912.19  8979.4 1908.59  9000.2 1911.56
  9031.4 1906.55  9062.5 1910.50  9191.1 1909.86  9415.9 1917.01  9660.6 1916.68
#Mann=3,-1,0
  1940.4    0.05       0  4987.5    0.05       0  5032.5    0.05       0
#XS Ineff=2,0
       0                 8313.00    0.00 1917.61
Permanent Ineff=
       F       F
Bank Sta=4987.5,5032.5
Exp/Cntr=0.3,0.1

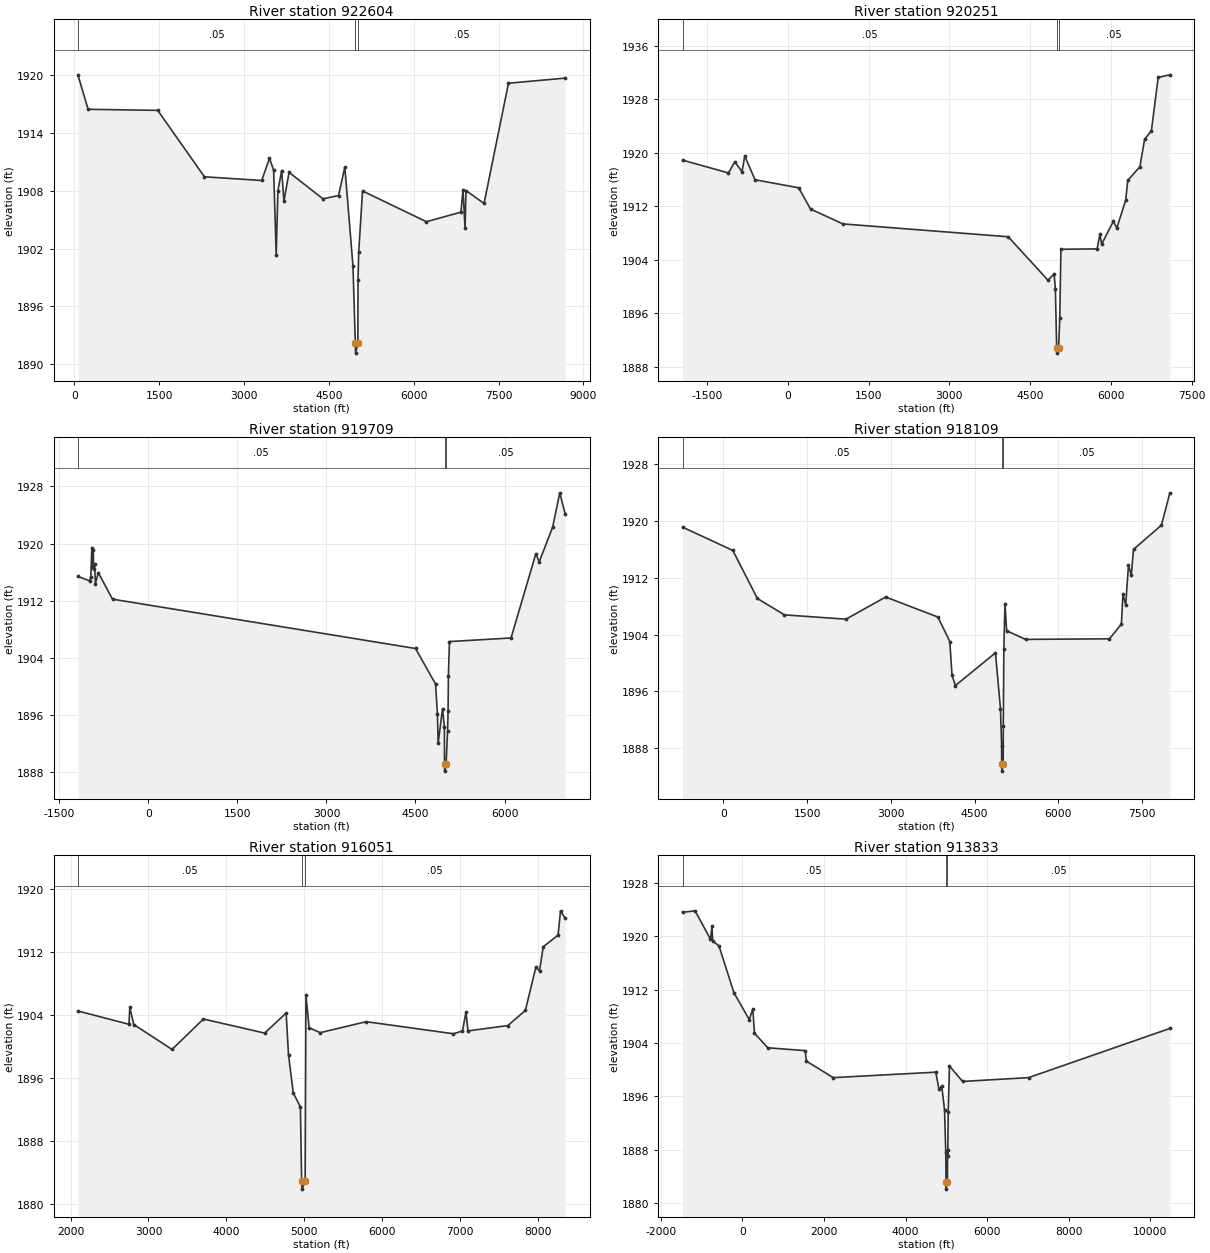
Type RM Length L Ch R = 1,922604,2353,2353,2353
BEGIN DESCRIPTION:
Mapping XS 3fd2b368
END DESCRIPTION:
XS GIS Cut Line= 6
      1385538.27      6980291.95      1386007.03      6978625.24
      1386875.09      6977201.63      1387031.34      6976871.77
      1387152.86      6976559.27      1384826.46      6972687.73
#Sta/Elev= 30
    62.8 1919.99   243.5 1916.42  1473.6 1916.31  2299.9 1909.43  3312.5 1909.05
  3450.0 1911.34  3523.1 1910.13  3568.6 1901.35  3598.4 1907.97  3665.1 1910.08
  3705.1 1906.91  3796.0 1909.89  4395.6 1907.15  4671.5 1907.49  4781.7 1910.45
  4926.0 1900.18  4967.5 1892.17  4971.3 1891.17  5012.5 1892.17  5015.0 1898.71
  5027.1 1901.62  5095.1 1907.96  6223.9 1904.78  6835.0 1905.77  6871.0 1908.07
  6907.9 1904.09  6923.4 1908.01  7243.3 1906.67  7675.0 1919.12  8678.6 1919.65
#Mann=3,-1,0
    62.8    0.05       0  4967.5    0.05       0  5012.5    0.05       0
Bank Sta=4967.5,5012.5
Exp/Cntr=0.3,0.1

Type RM Length L Ch R = 1,920251,542,542,542
BEGIN DESCRIPTION:
Mapping XS d5e58094
END DESCRIPTION:
XS GIS Cut Line= 5
      1385483.08      6981069.27      1386082.59      6978672.93
      1386957.59      6977193.76      1387665.92      6975256.26
      1388519.50      6972591.44
#Sta/Elev= 30
 -1954.8 1918.91 -1102.6 1917.00  -984.5 1918.66  -850.2 1917.18  -799.0 1919.53
  -608.0 1915.98   200.9 1914.78   422.4 1911.60  1023.8 1909.38  4092.8 1907.46
  4830.1 1900.98  4946.1 1901.88  4969.1 1899.67  4993.3 1890.87  4996.3 1890.07
  5029.3 1890.87  5051.1 1895.30  5072.1 1905.59  5744.2 1905.65  5796.7 1907.86
  5828.2 1906.35  6045.6 1909.77  6109.9 1908.76  6275.8 1912.95  6313.2 1915.88
  6538.2 1917.92  6626.2 1922.02  6752.2 1923.30  6878.2 1931.28  7095.1 1931.66
#Mann=3,-1,0
 -1954.8    0.05       0  4993.3    0.03       0  5029.3    0.05       0
Bank Sta=4993.3,5029.3
Exp/Cntr=0.3,0.1

Type RM Length L Ch R = 1,919709,1600,1600,1600
BEGIN DESCRIPTION:
Mapping XS 7bb9ddb9
END DESCRIPTION:
XS GIS Cut Line= 4
      1386103.42      6980610.43      1387582.59      6976860.43
      1388457.59      6974464.60      1388978.40      6972922.99
#Sta/Elev= 30
 -1186.3 1915.40  -990.2 1914.78  -968.7 1915.36  -951.5 1919.34  -946.1 1916.71
  -927.1 1919.07  -921.7 1916.44  -904.2 1917.12  -892.0 1914.38  -843.2 1915.93
  -603.2 1912.22  4500.9 1905.32  4838.3 1900.35  4870.2 1896.14  4882.0 1892.06
  4955.4 1896.91  4987.3 1894.33  4989.1 1889.17  4991.3 1888.17  5016.1 1889.17
  5040.6 1893.83  5049.3 1896.58  5054.6 1901.54  5072.5 1906.29  6109.7 1906.79
  6527.2 1918.55  6584.6 1917.44  6810.3 1922.28  6930.8 1927.09  7022.7 1924.09
#Mann=3,-1,0
 -1186.3    0.05       0  4989.1    0.05       0  5016.1    0.05       0
Bank Sta=4989.1,5016.1
Exp/Cntr=0.3,0.1

Type RM Length L Ch R = 1,918109,2058,2058,2058
BEGIN DESCRIPTION:
Mapping XS a7778102
END DESCRIPTION:
XS GIS Cut Line= 3
      1388978.42      6980464.59      1389790.92      6974964.60
      1389624.26      6971797.96
#Sta/Elev= 30
  -733.3 1919.16   167.5 1915.87   607.7 1909.09  1092.9 1906.78  2194.7 1906.17
  2905.7 1909.30  3842.4 1906.47  4054.7 1903.02  4095.1 1898.24  4155.8 1896.81
  4873.0 1901.42  4963.2 1893.51  4983.2 1888.32  4984.5 1885.73  4986.7 1884.73
  5011.5 1885.73  5013.2 1891.12  5023.2 1901.95  5043.3 1908.38  5073.3 1904.54
  5411.8 1903.32  6915.9 1903.40  7129.1 1905.47  7156.2 1909.67  7206.3 1908.22
  7256.3 1913.77  7306.4 1912.39  7346.5 1916.02  7847.2 1919.44  7997.4 1924.00
#Mann=3,-1,0
  -733.3    0.05       0  4984.5    0.05       0  5011.5    0.05       0
Bank Sta=4984.5,5011.5
Exp/Cntr=0.3,0.1

Type RM Length L Ch R = 1,916051,2218,2218,2218
BEGIN DESCRIPTION:
Mapping XS b38b774c
END DESCRIPTION:
XS GIS Cut Line= 4
      1390503.55      6978191.26      1390972.31      6975847.47
      1390781.34      6974805.80      1389861.80      6972151.29
#Sta/Elev= 30
  2094.0 1904.46  2750.0 1902.77  2760.2 1904.94  2811.2 1902.74  3302.7 1899.58
  3705.6 1903.44  4492.9 1901.65  4768.3 1904.20  4798.8 1898.87  4859.8 1894.05
  4951.3 1892.30  4967.5 1882.85  4971.3 1881.85  5012.5 1882.85  5022.5 1906.46
  5063.2 1902.34  5205.5 1901.71  5796.0 1903.10  6916.7 1901.57  7033.1 1901.92
  7077.8 1904.33  7103.7 1901.93  7615.2 1902.61  7840.7 1904.53  7975.0 1910.00
  8022.3 1909.55  8070.2 1912.61  8260.7 1914.09  8292.0 1917.17  8352.5 1916.20
#Mann=3,-1,0
  2094.0    0.05       0  4967.5    0.05       0  5012.5    0.05       0
Bank Sta=4967.5,5012.5
Exp/Cntr=0.3,0.1

Type RM Length L Ch R = 1,913833,4099,4099,4099
BEGIN DESCRIPTION:
Clear Fork Brazos Rv 217.0
END DESCRIPTION:
XS GIS Cut Line= 3
      1390305.02      6980537.96      1392705.00      6974538.00
      1391932.60      6969108.82
#Sta/Elev= 30
 -1467.7 1923.62 -1159.4 1923.84  -782.5 1919.58  -746.1 1921.49  -728.6 1919.33
  -573.8 1918.56  -207.6 1911.55   169.3 1907.51   255.5 1909.16   294.6 1905.48
   623.0 1903.29  1538.5 1902.86  1569.5 1901.28  2226.5 1898.81  4740.0 1899.63
  4818.1 1897.08  4886.7 1897.55  4955.4 1893.95  4985.0 1887.60  4990.9 1883.08
  4993.2 1882.08  5017.9 1883.08  5024.8 1882.85  5029.9 1888.02  5034.9 1887.04
  5045.0 1893.71  5075.3 1900.55  5398.5 1898.24  7013.7 1898.81 10478.3 1906.19
#Mann=3,-1,0
 -1467.7    0.05       0  4990.9    0.05       0  5017.9    0.05       0
Bank Sta=4990.9,5017.9
Exp/Cntr=0.3,0.1