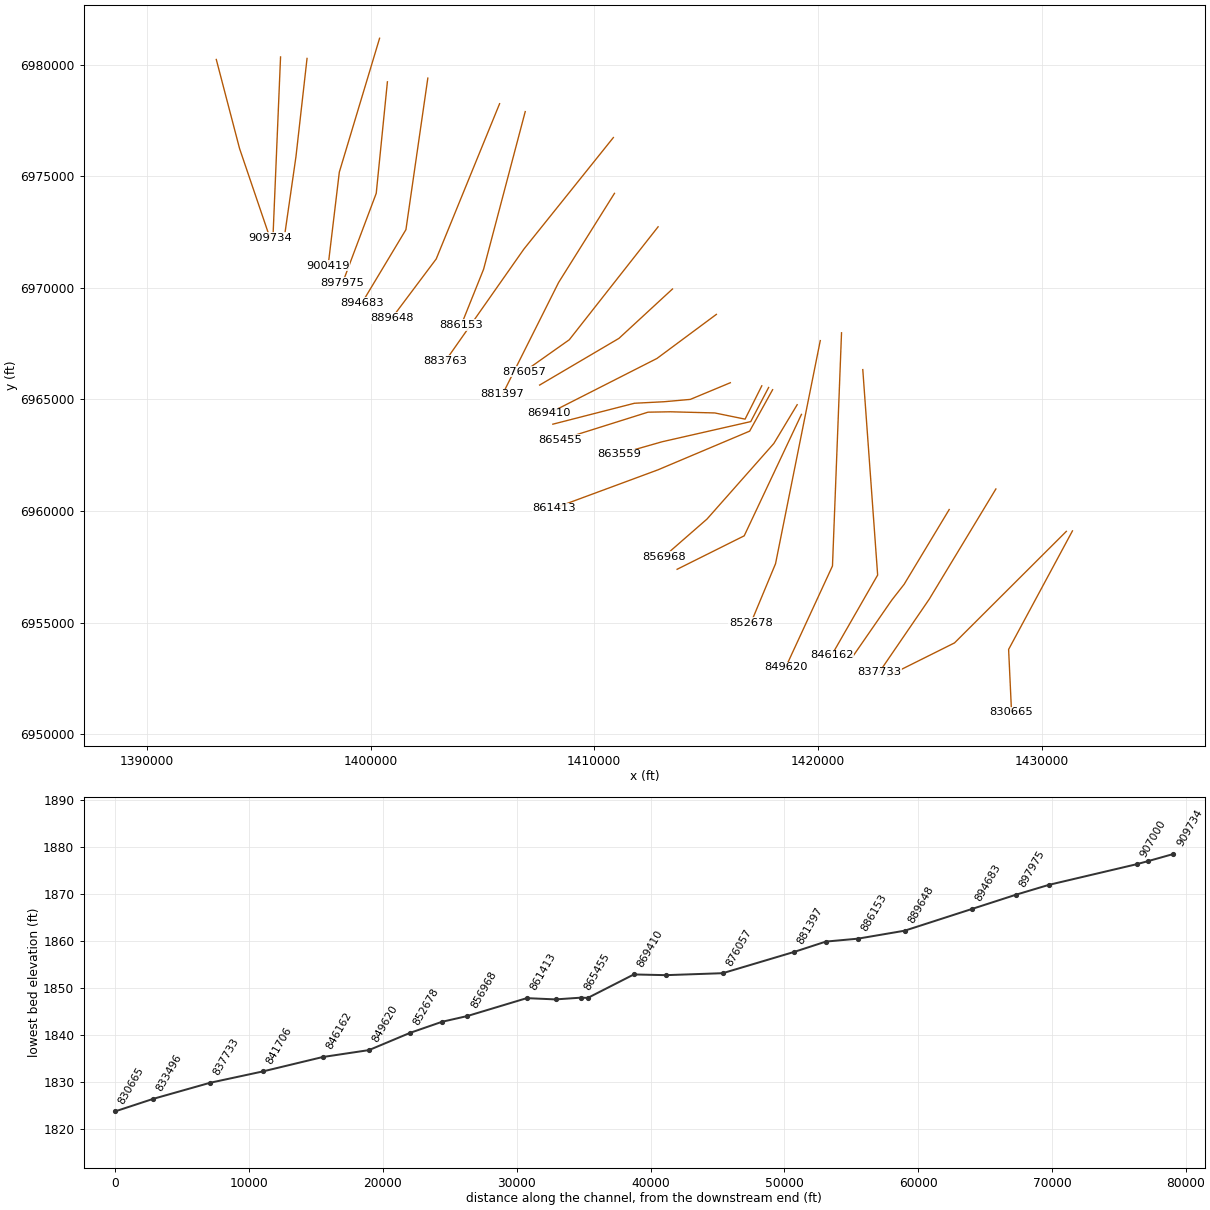
HEC-RAS study Clear Fork Brazos Rv.prj: Clear Fork Brazos Rv Base Level Engineering

--- Clear Fork Brazos Rv.g01 (geometry) --- (continued)

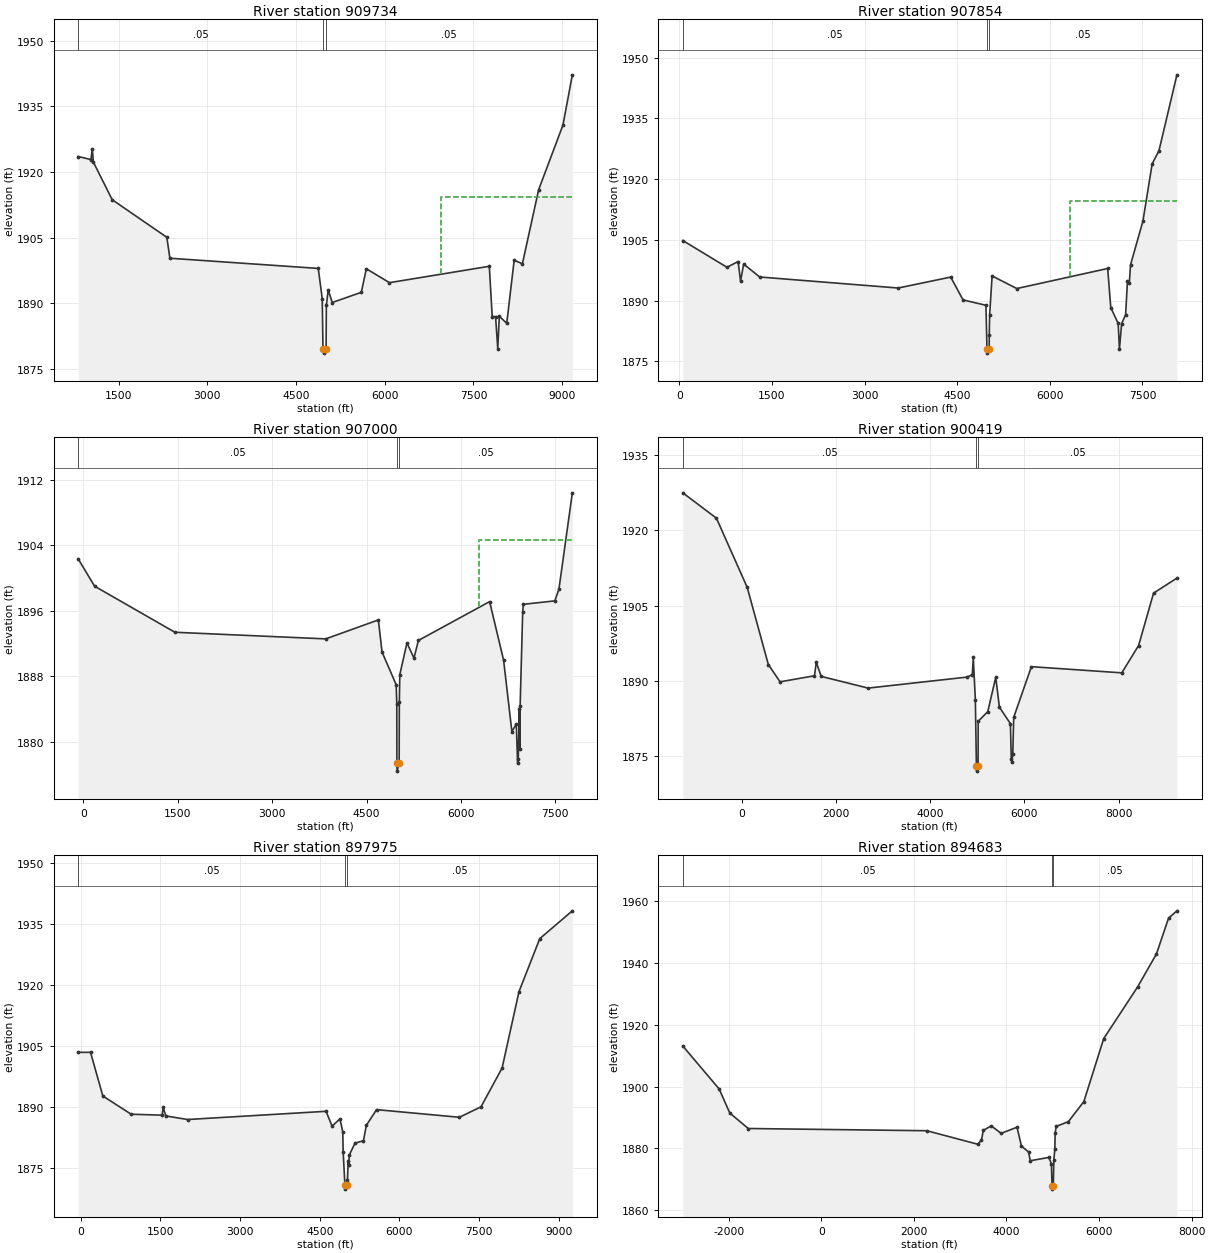
Type RM Length L Ch R = 1,909734,1880,1880,1880
BEGIN DESCRIPTION:
Clear Fork Brazos Rv 216.0
END DESCRIPTION:
XS GIS Cut Line= 3
      1393105.00      6980238.01      1394146.15      6976244.25
      1395505.01      6972237.97
#Sta/Elev= 30
   815.6 1923.54  1030.6 1922.84  1053.3 1925.32  1071.0 1922.27  1389.8 1913.66
  2314.1 1905.06  2365.7 1900.27  4875.3 1897.94  4942.8 1891.03  4954.8 1879.82
  4962.8 1879.56  4966.6 1878.56  5007.8 1879.56  5012.3 1889.47  5043.7 1893.02
  5111.8 1890.14  5603.7 1892.47  5688.6 1897.86  6080.1 1894.68  7768.8 1898.43
  7817.7 1886.93  7874.4 1886.92  7911.9 1879.58  7937.8 1886.99  8063.7 1885.39
  8189.3 1899.81  8328.5 1899.01  8603.1 1915.94  9014.9 1930.75  9173.3 1942.23
#Mann=3,-1,0
   815.6    0.05       0  4962.8    0.05       0  5007.8    0.05       0
#XS Ineff=2,0
       0                 6954.20    0.00 1914.21
Permanent Ineff=
       F       F
Bank Sta=4962.8,5007.8
Exp/Cntr=0.3,0.1

Type RM Length L Ch R = 1,907854,854,854,854
BEGIN DESCRIPTION:
Mapping XS c73e9b90
END DESCRIPTION:
XS GIS Cut Line= 3
      1395978.18      6980352.44      1395920.22      6978972.47
      1395642.45      6972357.89
#Sta/Elev= 30
    56.4 1904.86   771.5 1898.25   951.6 1899.67   991.7 1894.85  1041.7 1899.03
  1301.9 1895.85  3543.9 1893.13  4394.7 1895.83  4594.8 1890.18  4965.2 1888.87
  4982.0 1878.05  4985.0 1877.05  5018.0 1878.05  5019.1 1881.61  5025.2 1886.50
  5065.2 1896.11  5465.6 1893.00  6936.9 1897.95  6986.9 1888.29  7107.0 1884.38
  7127.1 1878.05  7162.5 1884.34  7227.2 1886.53  7257.2 1894.81  7287.2 1894.40
  7307.2 1898.88  7507.4 1909.64  7657.5 1923.81  7767.6 1927.05  8058.0 1945.78
#Mann=3,-1,0
    56.4    0.05       0  4982.0    0.05       0  5018.0    0.05       0
#XS Ineff=2,0
       0                 6333.50    0.00 1914.50
Permanent Ineff=
       F       F
Bank Sta=4982,5018
Exp/Cntr=0.3,0.1

Type RM Length L Ch R = 1,907000,6581,6581,6581
BEGIN DESCRIPTION:
Mapping XS 5fcaeda0
END DESCRIPTION:
XS GIS Cut Line= 4
      1397162.13      6980285.58      1396979.25      6978659.97
      1396666.75      6975882.19      1396180.64      6972496.78
#Sta/Elev= 30
   -81.1 1902.35   178.1 1899.02  1454.9 1893.38  3851.1 1892.57  4687.7 1894.89
  4746.3 1890.96  4970.6 1886.97  4980.7 1884.57  4982.0 1877.39  4985.0 1876.39
  5018.0 1877.39  5021.1 1884.80  5028.5 1888.20  5142.3 1892.08  5253.4 1890.22
  5324.1 1892.38  6455.6 1897.13  6677.9 1889.96  6809.2 1881.23  6879.9 1882.15
  6900.1 1877.39  6910.3 1877.85  6927.9 1883.97  6933.0 1879.11  6940.6 1884.37
  6981.0 1895.80  6991.1 1896.80  7492.2 1897.22  7556.8 1898.65  7770.2 1910.44
#Mann=3,-1,0
   -81.1    0.05       0  4982.0    0.05       0  5018.0    0.05       0
#XS Ineff=2,0
       0                 6294.70    0.00 1904.63
Permanent Ineff=
       F       F
Bank Sta=4982,5018
Exp/Cntr=0.3,0.1

Type RM Length L Ch R = 1,900419,2444,2444,2444
BEGIN DESCRIPTION:
Clear Fork Brazos Rv 214.0
END DESCRIPTION:
XS GIS Cut Line= 3
      1400405.01      6981188.04      1398605.00      6975188.00
      1398103.43      6970985.45
#Sta/Elev= 30
 -1255.6 1927.47  -541.3 1922.41   112.1 1908.62   561.1 1893.23   810.8 1889.78
  1541.6 1890.99  1579.9 1893.69  1684.3 1890.86  2680.4 1888.53  4789.4 1890.73
  4893.8 1891.22  4914.7 1894.66  4959.0 1886.20  4981.3 1872.97  4984.3 1871.97
  5017.3 1872.97  5018.7 1881.90  5222.4 1883.83  5392.4 1890.68  5469.8 1884.73
  5703.5 1881.44  5722.3 1874.41  5733.7 1873.74  5753.9 1875.34  5774.0 1882.70
  6149.7 1892.80  8070.2 1891.57  8426.9 1897.02  8745.0 1907.47  9241.0 1910.47
#Mann=3,-1,0
 -1255.6    0.05       0  4981.3    0.05       0  5017.3    0.05       0
Bank Sta=4981.3,5017.3
Exp/Cntr=0.3,0.1

Type RM Length L Ch R = 1,897975,3292,3292,3292
BEGIN DESCRIPTION:
Clear Fork Brazos Rv 213.0
END DESCRIPTION:
XS GIS Cut Line= 3
      1400755.00      6979237.97      1400255.00      6974238.00
      1398755.00      6970238.01
#Sta/Elev= 30
   -44.1 1903.52   187.0 1903.52   418.2 1892.79   950.8 1888.30  1533.7 1888.07
  1553.8 1889.96  1604.0 1887.88  2013.6 1887.00  4619.0 1889.02  4732.1 1885.36
  4880.3 1887.16  4933.1 1883.95  4940.6 1879.04  4973.3 1870.88  4976.3 1869.88
  5009.3 1870.88  5020.9 1872.05  5034.2 1876.68  5044.9 1875.89  5056.5 1878.26
  5161.5 1881.17  5322.6 1881.79  5376.0 1885.56  5569.1 1889.43  7126.6 1887.55
  7534.2 1890.12  7931.2 1899.67  8248.9 1918.45  8639.6 1931.48  9252.8 1938.32
#Mann=3,-1,0
   -44.1    0.05       0  4973.3    0.05       0  5009.3    0.05       0
Bank Sta=4973.3,5009.3
Exp/Cntr=0.3,0.1

Type RM Length L Ch R = 1,894683,5035,5035,5035
BEGIN DESCRIPTION:
Clear Fork Brazos Rv 212.0
END DESCRIPTION:
XS GIS Cut Line= 3
      1402561.76      6979402.14      1401582.59      6972610.43
      1399625.29      6969341.32
#Sta/Elev= 30
 -2990.3 1913.08 -2205.1 1899.20 -1975.8 1891.44 -1576.5 1886.43  2280.4 1885.71
  3379.0 1881.35  3459.9 1882.64  3500.3 1885.84  3672.0 1887.27  3886.1 1884.86
  4228.5 1886.85  4323.8 1880.75  4477.4 1878.84  4514.4 1876.01  4913.0 1877.08
  4971.4 1875.10  4984.5 1867.84  4986.8 1866.84  5011.5 1867.84  5023.9 1876.30
  5045.3 1879.88  5051.7 1884.90  5075.0 1887.11  5337.0 1888.64  5671.4 1895.12
  6101.2 1915.49  6832.4 1932.17  7240.7 1942.87  7501.3 1954.41  7681.9 1956.77
#Mann=3,-1,0
 -2990.3    0.05       0  4984.5    0.05       0  5011.5    0.05       0
Bank Sta=4984.5,5011.5
Exp/Cntr=0.3,0.1

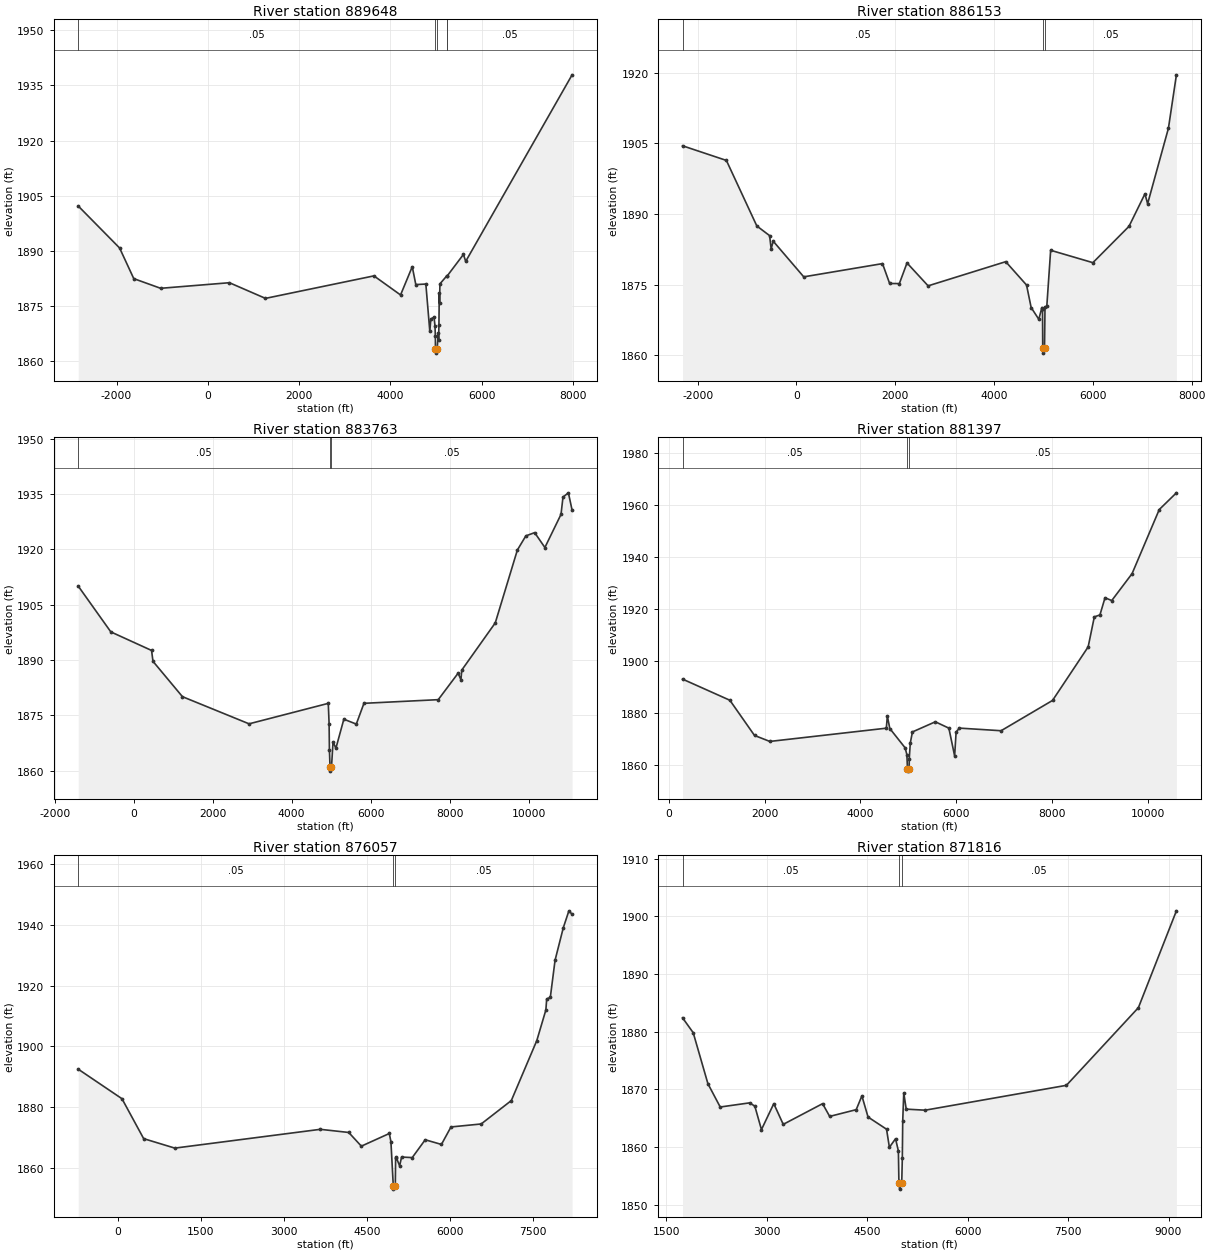
Type RM Length L Ch R = 1,889648,3495,3495,3495
BEGIN DESCRIPTION:
Clear Fork Brazos Rv 211.0
END DESCRIPTION:
XS GIS Cut Line= 3
      1405770.08      6978256.24      1402936.76      6971297.93
      1400957.90      6968652.51
#Sta/Elev= 30
 -2838.5 1902.21 -1932.4 1890.79 -1622.1 1882.46 -1033.5 1879.83   472.6 1881.35
  1262.5 1877.09  3637.9 1883.21  4221.0 1878.02  4477.5 1885.71  4555.1 1880.84
  4775.0 1880.99  4861.8 1868.13  4883.3 1871.41  4954.2 1872.02  4975.0 1869.64
  4983.4 1866.80  4985.2 1863.20  4988.2 1862.20  5021.2 1863.20  5048.0 1867.58
  5054.2 1865.69  5061.6 1869.90  5068.8 1878.57  5075.1 1875.80  5083.4 1881.04
  5230.0 1883.16  5245.1 1883.23  5598.2 1889.04  5648.2 1887.16  7978.2 1937.89
#Mann=5,-1,0
 -2838.5    0.05       0  4985.2    0.05       0  5021.2    0.05       0
  5230.0    0.12       0  5245.1    0.05       0
Bank Sta=4985.2,5021.2
Exp/Cntr=0.3,0.1

Type RM Length L Ch R = 1,886153,2390,2390,2390
BEGIN DESCRIPTION:
Clear Fork Brazos Rv 210.0
END DESCRIPTION:
XS GIS Cut Line= 3
      1406915.91      6977902.06      1405055.00      6970838.00
      1404055.02      6968338.04
#Sta/Elev= 30
 -2306.0 1904.51 -1418.4 1901.40  -802.3 1887.49  -543.8 1885.44  -512.0 1882.61
  -471.4 1884.27   147.5 1876.69  1741.6 1879.50  1886.4 1875.28  2082.9 1875.26
  2238.0 1879.64  2665.3 1874.78  4236.3 1879.91  4657.8 1874.95  4750.9 1870.18
  4906.0 1867.68  4968.0 1870.18  4981.5 1869.77  4985.4 1861.50  4988.4 1860.50
  5021.4 1861.50  5031.4 1870.32  5067.7 1870.41  5145.8 1882.33  6000.7 1879.70
  6731.7 1887.41  7054.8 1894.31  7108.7 1892.21  7530.1 1908.24  7691.6 1919.57
#Mann=3,-1,0
 -2306.0    0.05       0  4985.4    0.05       0  5021.4    0.05       0
Bank Sta=4985.4,5021.4
Exp/Cntr=0.3,0.1

Type RM Length L Ch R = 1,883763,2366,2366,2366
BEGIN DESCRIPTION:
Clear Fork Brazos Rv 209.0
END DESCRIPTION:
XS GIS Cut Line= 3
      1410854.99      6976737.99      1406855.00      6971738.00
      1403355.00      6966737.99
#Sta/Elev= 30
 -1403.8 1910.03  -578.6 1897.62   453.1 1892.59   489.1 1889.64  1235.1 1880.06
  2922.3 1872.70  4928.1 1878.25  4948.9 1872.75  4956.9 1865.70  4973.1 1860.88
  4976.1 1859.88  5009.1 1860.88  5048.6 1867.83  5121.4 1866.08  5322.4 1873.95
  5638.0 1872.63  5831.5 1878.26  7713.1 1879.25  8216.2 1886.43  8287.7 1884.64
  8308.6 1887.27  9157.0 1900.06  9716.7 1919.81  9931.2 1923.64 10154.4 1924.52
 10413.4 1920.49 10821.8 1929.47 10872.0 1934.16 11008.9 1935.31 11102.6 1930.61
#Mann=3,-1,0
 -1403.8    0.05       0  4973.1    0.05       0  5009.1    0.05       0
Bank Sta=4973.1,5009.1
Exp/Cntr=0.3,0.1

Type RM Length L Ch R = 1,881397,5340,5340,5340
BEGIN DESCRIPTION:
Clear Fork Brazos Rv 208.0
END DESCRIPTION:
XS GIS Cut Line= 3
      1410904.98      6974237.96      1408405.00      6970238.00
      1405905.01      6965238.01
#Sta/Elev= 30
   288.9 1893.01  1276.5 1884.89  1790.6 1871.38  2110.2 1869.08  4541.8 1874.17
  4563.0 1878.80  4614.9 1874.03  4934.5 1866.62  4970.5 1864.01  4983.2 1858.68
  4986.2 1857.68  5019.2 1858.68  5019.8 1862.34  5042.2 1868.50  5086.9 1872.73
  5564.9 1876.62  5847.2 1874.18  5967.4 1863.51  5998.1 1872.64  6065.2 1874.20
  6937.2 1873.19  8010.6 1884.82  8754.1 1905.38  8882.6 1916.89  9000.0 1917.66
  9106.2 1924.26  9246.0 1923.16  9670.8 1933.51 10238.2 1958.12 10596.0 1964.53
#Mann=3,-1,0
   288.9    0.05       0  4983.2    0.05       0  5019.2    0.05       0
Bank Sta=4983.2,5019.2
Exp/Cntr=0.3,0.1

Type RM Length L Ch R = 1,876057,4241,4241,4241
BEGIN DESCRIPTION:
Clear Fork Brazos Rv 207.0
END DESCRIPTION:
XS GIS Cut Line= 3
      1412854.99      6972737.99      1408885.73      6967676.54
      1406855.03      6966238.02
#Sta/Elev= 30
  -716.6 1892.53    73.5 1882.83   465.3 1869.72  1028.1 1866.61  3656.0 1872.78
  4169.5 1871.75  4397.3 1867.25  4902.6 1871.41  4931.5 1868.72  4974.5 1854.14
  4977.5 1853.14  5010.5 1854.14  5016.5 1863.28  5024.6 1863.68  5088.8 1860.79
  5124.1 1863.67  5316.6 1863.50  5550.8 1869.35  5844.0 1867.82  6016.3 1873.56
  6562.1 1874.54  7106.6 1882.23  7566.8 1901.94  7730.5 1911.99  7745.2 1915.59
  7810.5 1916.09  7896.6 1928.33  8045.5 1939.00  8146.4 1944.54  8204.2 1943.40
#Mann=3,-1,0
  -716.6    0.05       0  4974.5    0.05       0  5010.5    0.05       0
Bank Sta=4974.5,5010.5
Exp/Cntr=0.3,0.1

Type RM Length L Ch R = 1,871816,2406,2406,2406
BEGIN DESCRIPTION:
Clear Fork Brazos Rv 206.0
END DESCRIPTION:
XS GIS Cut Line= 3
      1413497.55      6969950.74      1411105.00      6967738.00
      1407560.00      6965645.14
#Sta/Elev= 30
  1742.3 1882.43  1901.7 1879.84  2121.1 1871.00  2304.8 1866.96  2743.7 1867.68
  2821.8 1867.11  2920.6 1863.04  3104.9 1867.54  3246.1 1863.95  3833.5 1867.54
  3939.5 1865.33  4335.8 1866.50  4420.9 1868.89  4512.7 1865.22  4788.9 1863.11
  4831.4 1859.97  4923.3 1861.46  4965.8 1859.33  4973.1 1854.18  4979.6 1853.72
  4982.6 1852.72  5015.6 1853.72  5024.4 1858.08  5030.5 1864.55  5046.1 1869.42
  5082.5 1866.59  5366.1 1866.41  7475.2 1870.72  8550.3 1884.19  9117.9 1900.98
#Mann=3,-1,0
  1742.3    0.05       0  4979.6    0.05       0  5015.6    0.05       0
Bank Sta=4979.6,5015.6
Exp/Cntr=0.3,0.1

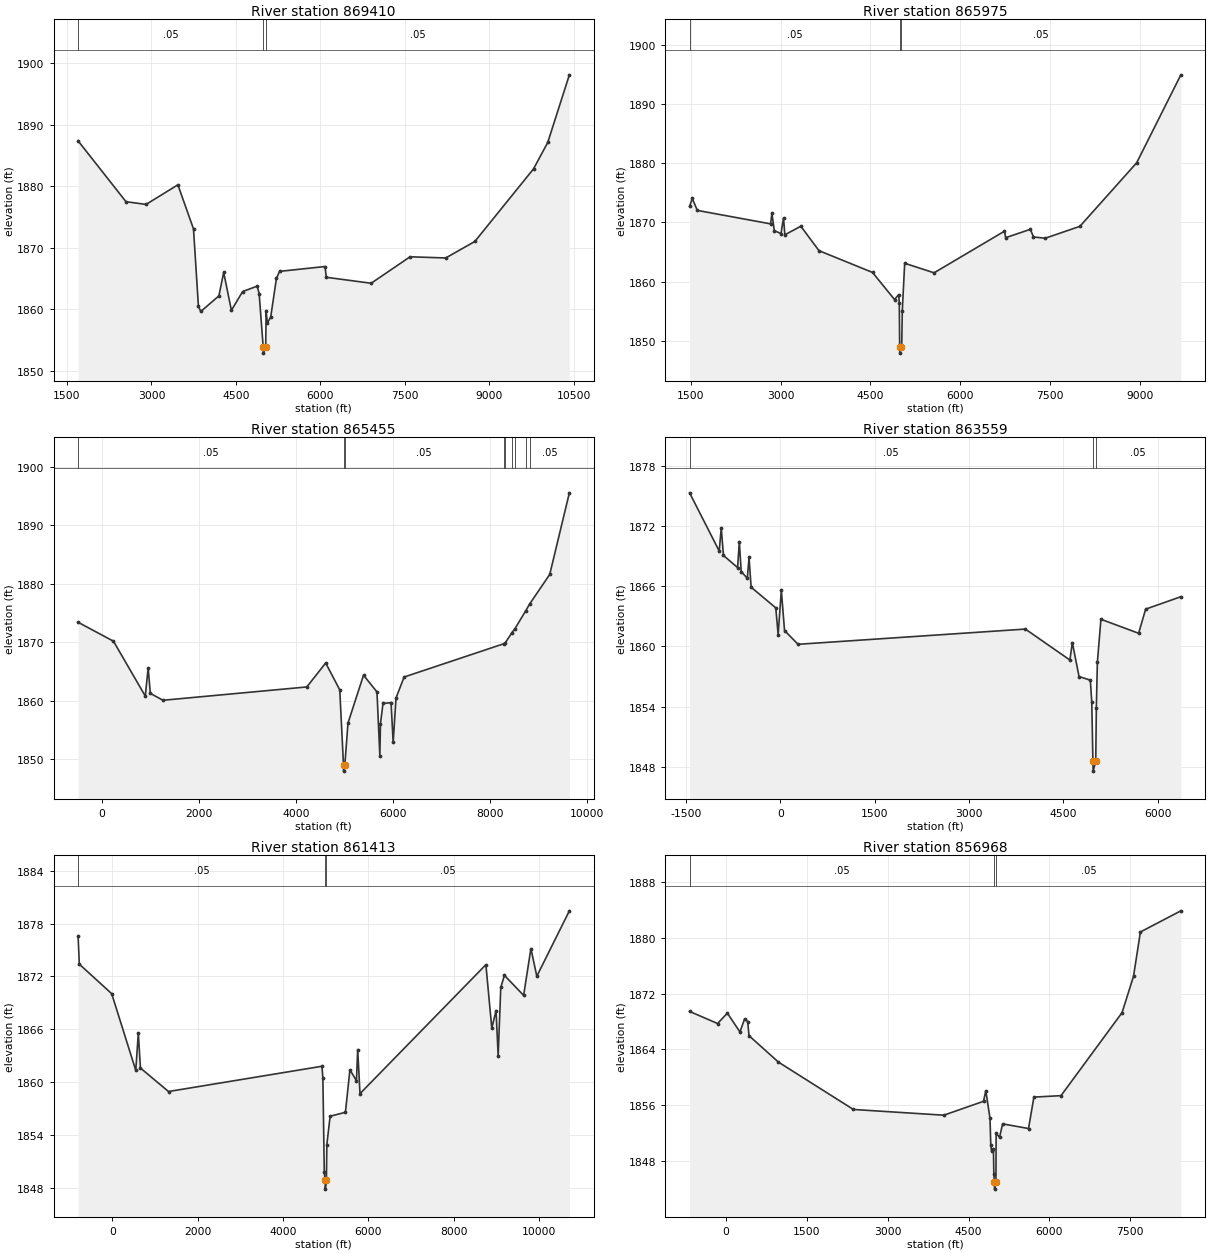
Type RM Length L Ch R = 1,869410,3435,3435,3435
BEGIN DESCRIPTION:
Clear Fork Brazos Rv 205.0
END DESCRIPTION:
XS GIS Cut Line= 3
      1415459.51      6968812.61      1412805.00      6966838.00
      1407978.36      6964378.64
#Sta/Elev= 30
  1697.3 1887.35  2547.7 1877.47  2904.3 1877.03  3469.6 1880.21  3746.9 1873.05
  3834.2 1860.48  3876.3 1859.64  4197.5 1862.16  4283.0 1865.98  4419.9 1859.82
  4619.3 1862.87  4877.4 1863.75  4912.9 1862.55  4984.6 1853.87  4988.4 1852.87
  5029.6 1853.87  5036.3 1859.64  5058.5 1857.79  5117.9 1858.71  5219.8 1865.00
  5275.1 1866.15  6083.1 1866.94  6105.6 1865.19  6902.4 1864.22  7593.2 1868.52
  8226.8 1868.33  8743.9 1871.01  9786.8 1882.81 10039.1 1887.10 10422.8 1898.08
#Mann=3,-1,0
  1697.3    0.05       0  4984.6    0.05       0  5029.6    0.05       0
Bank Sta=4984.6,5029.6
Exp/Cntr=0.3,0.1

Type RM Length L Ch R = 1,865975,520,520,520
BEGIN DESCRIPTION:
Mapping XS bf599f95
END DESCRIPTION:
XS GIS Cut Line= 5
      1416084.36      6965749.33      1414296.13      6965002.79
      1413132.94      6964898.63      1411796.13      6964829.18
      1408150.30      6963891.68
#Sta/Elev= 30
  1480.5 1872.73  1525.7 1874.06  1609.8 1872.04  2834.4 1869.76  2856.0 1871.53
  2896.3 1868.61  3007.8 1868.12  3050.0 1870.74  3072.8 1867.91  3339.1 1869.36
  3642.8 1865.22  4538.0 1861.53  4904.5 1856.95  4974.6 1857.78  4984.6 1856.38
  4990.9 1848.87  4993.2 1847.87  5017.9 1848.87  5024.7 1848.92  5034.7 1855.08
  5074.7 1863.09  5565.4 1861.47  6741.6 1868.52  6762.3 1867.42  7175.3 1868.84
  7226.9 1867.54  7423.1 1867.33  8002.0 1869.34  8951.3 1880.11  9689.2 1895.00
#Mann=3,-1,0
  1480.5    0.05       0  4990.9   0.035       0  5017.9    0.05       0
Bank Sta=4990.9,5017.9
Exp/Cntr=0.3,0.1

Type RM Length L Ch R = 1,865455,1896,1896,1896
BEGIN DESCRIPTION:
Mapping XS 60ee173d
END DESCRIPTION:
XS GIS Cut Line= 6
      1417490.58      6965610.44      1416744.05      6964117.38
      1415389.88      6964395.15      1413410.71      6964447.24
      1412403.77      6964429.88      1408498.79      6963197.64
#Sta/Elev= 30
  -492.4 1873.40   237.1 1870.16   893.2 1860.77   952.6 1865.58   997.3 1861.23
  1258.7 1860.05  4224.7 1862.33  4614.8 1866.43  4904.9 1861.83  4982.0 1848.92
  4984.2 1847.92  5009.0 1848.92  5074.9 1856.16  5395.0 1864.34  5672.4 1861.48
  5731.8 1850.58  5744.2 1856.00  5796.5 1859.50  5963.5 1859.64  6006.3 1852.84
  6065.7 1860.46  6232.7 1864.03  8286.7 1869.72  8311.5 1869.79  8457.3 1871.64
  8516.4 1872.27  8742.2 1875.39  8820.6 1876.52  9236.0 1881.59  9641.0 1895.56
#Mann=9,-1,0
  -492.4    0.05       0  4982.0    0.05       0  5009.0    0.05       0
  8286.7    0.12       0  8311.5    0.05       0  8457.3    0.12       0
  8516.4    0.05       0  8742.2    0.12       0  8820.6    0.05       0
Bank Sta=4982,5009
Exp/Cntr=0.3,0.1

Type RM Length L Ch R = 1,863559,2146,2146,2146
BEGIN DESCRIPTION:
Mapping XS 1954be39
END DESCRIPTION:
XS GIS Cut Line= 4
      1417795.25      6965535.01      1416996.61      6964007.19
      1413038.28      6963104.41      1411093.83      6962548.85
#Sta/Elev= 30
 -1441.4 1875.33  -970.9 1869.52  -938.1 1871.83  -903.2 1869.08  -678.8 1867.87
  -651.1 1870.45  -621.1 1867.47  -524.3 1866.80  -496.6 1868.88  -463.7 1865.91
   -72.0 1863.85   -34.3 1861.17    16.3 1865.60    67.3 1861.58   282.6 1860.21
  3894.3 1861.73  4601.6 1858.64  4640.6 1860.38  4747.2 1856.99  4926.6 1856.63
  4949.2 1854.44  4967.5 1848.55  4971.3 1847.55  5012.5 1848.55  5022.0 1853.89
  5038.4 1858.42  5094.8 1862.71  5693.6 1861.31  5805.4 1863.72  6364.8 1864.96
#Mann=3,-1,0
 -1441.4    0.05       0  4967.5    0.05       0  5012.5    0.05       0
Bank Sta=4967.5,5012.5
Exp/Cntr=0.3,0.1

Type RM Length L Ch R = 1,861413,4445,4445,4445
BEGIN DESCRIPTION:
Clear Fork Brazos Rv 201.0
END DESCRIPTION:
XS GIS Cut Line= 4
      1417974.28      6965436.97      1416947.43      6963579.80
      1412844.06      6961843.21      1408209.36      6960124.72
#Sta/Elev= 30
  -805.8 1876.53  -777.3 1873.38   -18.5 1870.03   546.7 1861.31   606.3 1865.56
   655.7 1861.58  1314.5 1858.91  4913.2 1861.78  4934.9 1860.40  4967.5 1849.71
  4989.8 1848.82  4992.0 1847.82  5016.8 1848.82  5027.9 1852.89  5104.4 1856.10
  5463.1 1856.55  5568.7 1861.38  5721.7 1860.14  5750.8 1863.67  5804.9 1858.67
  8757.3 1873.32  8896.0 1866.11  8995.8 1868.11  9045.3 1862.95  9106.6 1870.74
  9192.4 1872.11  9642.6 1869.83  9813.2 1875.15  9951.8 1872.01 10715.1 1879.44
#Mann=3,-1,0
  -805.8    0.05       0  4989.8    0.05       0  5016.8    0.05       0
Bank Sta=4989.8,5016.8
Exp/Cntr=0.3,0.1

Type RM Length L Ch R = 1,856968,1884,1884,1884
BEGIN DESCRIPTION:
Mapping XS daae4a90
END DESCRIPTION:
XS GIS Cut Line= 4
      1419071.62      6964763.69      1418029.96      6963027.59
      1415043.84      6959642.18      1413100.93      6957942.12
#Sta/Elev= 30
  -678.3 1869.45  -158.5 1867.72    23.4 1869.21   256.6 1866.51   342.9 1868.37
   401.2 1868.00   424.6 1865.98   971.9 1862.19  2362.5 1855.41  4041.5 1854.59
  4778.6 1856.58  4821.3 1858.10  4899.1 1854.13  4913.3 1850.37  4927.5 1849.41
  4962.7 1849.78  4970.2 1846.12  4981.8 1845.00  4984.1 1844.00  5008.8 1845.00
  5012.7 1851.98  5076.5 1851.43  5132.7 1853.35  5614.4 1852.68  5713.9 1857.18
  6217.4 1857.39  7350.7 1869.28  7563.3 1874.48  7691.4 1880.83  8442.2 1883.86
#Mann=3,-1,0
  -678.3    0.05       0  4981.8    0.05       0  5008.8    0.05       0
Bank Sta=4981.8,5008.8
Exp/Cntr=0.3,0.1

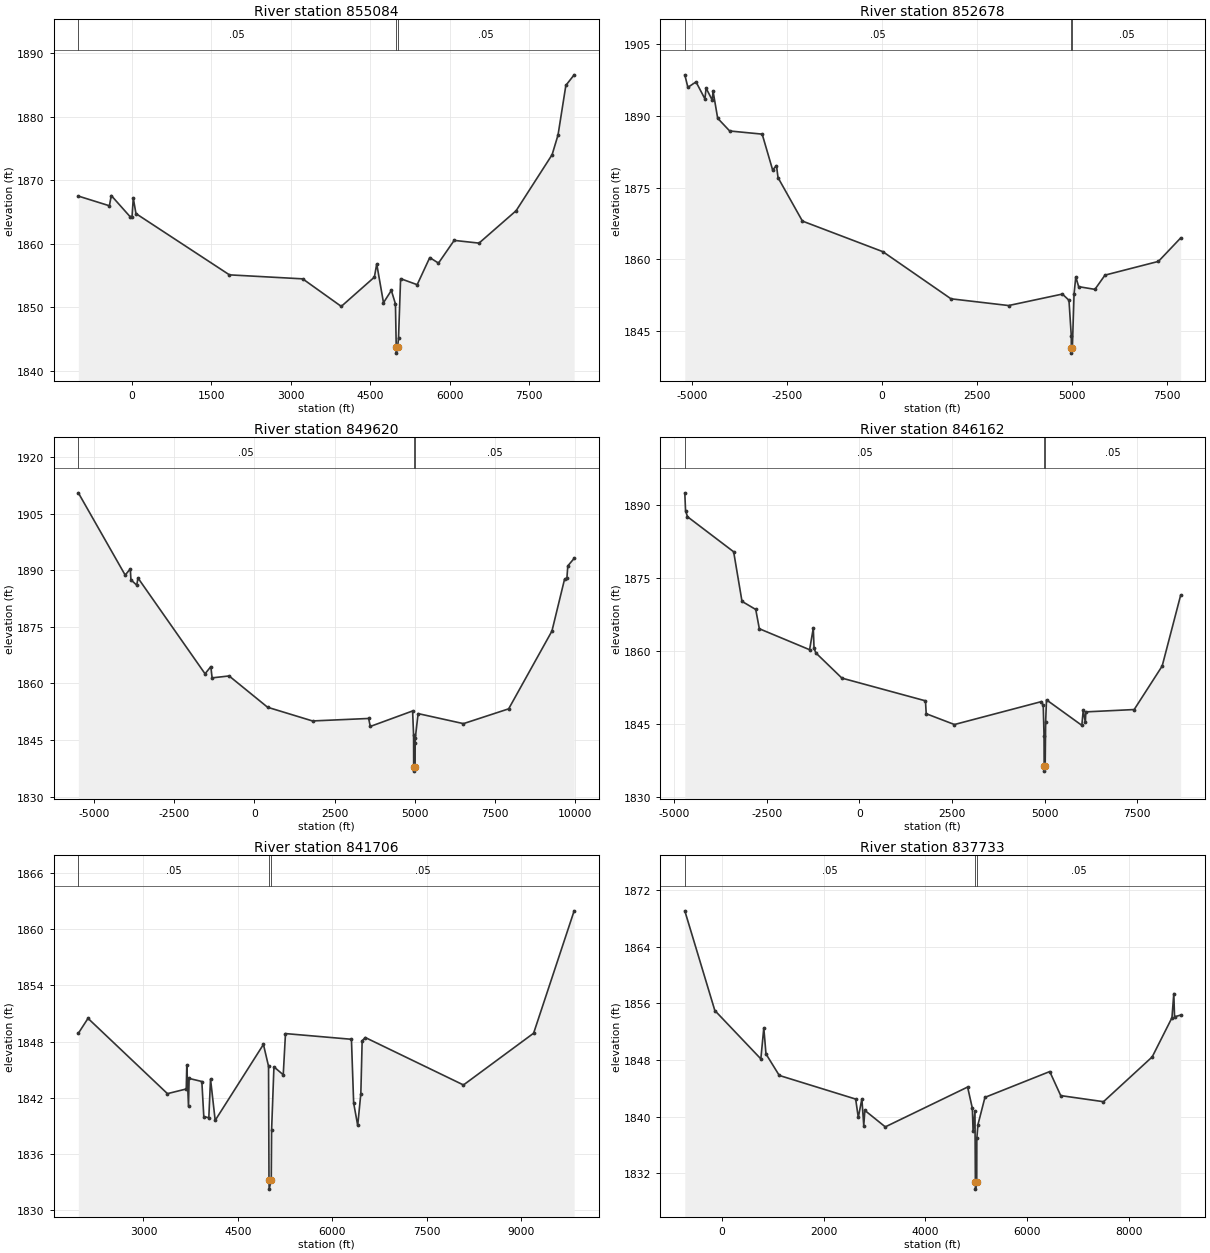
Type RM Length L Ch R = 1,855084,2406,2406,2406
BEGIN DESCRIPTION:
Clear Fork Brazos Rv 200.0
END DESCRIPTION:
XS GIS Cut Line= 3
      1419262.60      6964329.69      1416705.00      6958888.00
      1413704.97      6957387.98
#Sta/Elev= 30
 -1012.3 1867.52  -424.8 1865.99  -390.5 1867.61   -37.4 1864.30     2.7 1864.29
    25.5 1867.20    76.6 1864.76  1842.2 1855.11  3226.3 1854.48  3955.3 1850.14
  4580.6 1854.75  4624.8 1856.83  4752.7 1850.72  4901.0 1852.66  4978.4 1850.53
  4993.3 1843.78  4995.6 1842.78  5020.3 1843.78  5036.8 1845.19  5075.9 1854.51
  5389.0 1853.56  5626.6 1857.83  5791.5 1856.96  6087.8 1860.54  6557.3 1860.11
  7258.9 1865.22  7938.1 1874.04  8049.9 1877.14  8198.0 1884.96  8354.6 1886.62
#Mann=3,-1,0
 -1012.3    0.05       0  4993.3    0.05       0  5020.3    0.05       0
Bank Sta=4993.3,5020.3
Exp/Cntr=0.3,0.1

Type RM Length L Ch R = 1,852678,3058,3058,3058
BEGIN DESCRIPTION:
Clear Fork Brazos Rv 199.0
END DESCRIPTION:
XS GIS Cut Line= 3
      1420104.99      6967637.97      1418105.00      6957638.00
      1417004.47      6954985.45
#Sta/Elev= 30
 -5198.0 1898.59 -5116.4 1895.97 -4902.3 1897.11 -4667.7 1893.56 -4637.1 1895.81
 -4474.0 1893.29 -4453.6 1895.20 -4331.2 1889.51 -4015.1 1886.85 -3158.4 1886.19
 -2883.1 1878.71 -2781.1 1879.60 -2740.3 1877.09 -2097.8 1868.01    23.4 1861.61
  1818.2 1851.76  3337.7 1850.35  4755.3 1852.75  4928.6 1851.45  4989.8 1843.96
  4990.9 1841.40  4993.2 1840.40  5017.9 1841.40  5062.4 1852.72  5108.3 1856.34
  5184.1 1854.30  5612.5 1853.73  5878.3 1856.71  7286.6 1859.58  7871.8 1864.47
#Mann=3,-1,0
 -5198.0    0.05       0  4990.9    0.05       0  5017.9    0.05       0
Bank Sta=4990.9,5017.9
Exp/Cntr=0.3,0.1

Type RM Length L Ch R = 1,849620,3458,3458,3458
BEGIN DESCRIPTION:
Clear Fork Brazos Rv 198.0
END DESCRIPTION:
XS GIS Cut Line= 3
      1421055.00      6967988.05      1420650.30      6957537.51
      1418555.00      6952988.00
#Sta/Elev= 30
 -5493.8 1910.51 -4032.7 1888.71 -3872.5 1890.35 -3852.5 1887.45 -3672.4 1886.04
 -3632.4 1887.93 -1540.8 1862.54 -1360.7 1864.45 -1320.6 1861.46  -790.2 1861.97
   410.7 1853.67  1811.7 1850.04  3563.0 1850.70  3613.1 1848.58  4934.1 1852.69
  4964.6 1846.22  4967.4 1838.14  4976.0 1837.74  4979.0 1836.74  5012.0 1837.74
  5013.3 1844.19  5019.1 1845.58  5105.2 1851.99  6520.5 1849.33  7930.3 1853.25
  9279.8 1873.86  9672.6 1887.57  9747.0 1887.93  9775.5 1891.14  9973.4 1893.14
#Mann=3,-1,0
 -5493.8    0.05       0  4976.0   0.035       0  5012.0    0.05       0
Bank Sta=4976,5012
Exp/Cntr=0.3,0.1

Type RM Length L Ch R = 1,846162,4456,4456,4456
BEGIN DESCRIPTION:
Clear Fork Brazos Rv 197.0
END DESCRIPTION:
XS GIS Cut Line= 3
      1422005.00      6966337.95      1422669.58      6957129.67
      1420607.09      6953525.51
#Sta/Elev= 30
 -4712.6 1892.47 -4692.6 1888.82 -4640.3 1887.56 -3393.6 1880.35 -3168.6 1870.16
 -2797.7 1868.49 -2700.4 1864.53 -1343.9 1860.22 -1243.6 1864.66 -1223.6 1860.49
 -1174.4 1859.56  -471.1 1854.38  1784.2 1849.71  1804.3 1847.06  2566.2 1844.84
  4913.3 1849.55  4963.4 1848.77  4985.0 1842.52  4988.5 1836.26  4990.7 1835.26
  5015.5 1836.26  5028.5 1845.41  5051.6 1849.91  6005.4 1844.67  6042.4 1847.73
  6100.0 1845.30  6113.3 1847.44  7418.6 1847.92  8173.9 1856.86  8672.2 1871.40
#Mann=3,-1,0
 -4712.6    0.05       0  4988.5    0.05       0  5015.5    0.05       0
Bank Sta=4988.5,5015.5
Exp/Cntr=0.3,0.1

Type RM Length L Ch R = 1,841706,3973,3973,3973
BEGIN DESCRIPTION:
Mapping XS 8a478eac
END DESCRIPTION:
XS GIS Cut Line= 4
      1425868.17      6960066.26      1423854.25      6956715.52
      1423298.70      6956003.72      1421562.59      6953486.36
#Sta/Elev= 30
  1965.7 1848.88  2119.3 1850.48  3380.2 1842.42  3678.8 1842.92  3687.2 1845.50
  3714.4 1841.07  3724.1 1844.05  3926.2 1843.72  3957.2 1839.97  4036.9 1839.84
  4064.1 1843.98  4137.9 1839.56  4903.8 1847.69  4985.0 1845.35  4992.0 1833.20
  4995.0 1832.20  5028.0 1833.20  5033.6 1838.53  5070.5 1845.29  5218.2 1844.44
  5253.8 1848.85  6300.7 1848.24  6336.0 1841.42  6400.2 1839.02  6450.0 1842.43
  6470.8 1848.08  6520.5 1848.43  8078.9 1843.35  9192.5 1848.89  9836.0 1861.99
#Mann=3,-1,0
  1965.7    0.05       0  4992.0    0.05       0  5028.0    0.05       0
Bank Sta=4992,5028
Exp/Cntr=0.3,0.1

Type RM Length L Ch R = 1,837733,4237,4237,4237
BEGIN DESCRIPTION:
Clear Fork Brazos Rv 196.0
END DESCRIPTION:
XS GIS Cut Line= 3
      1427955.02      6960988.03      1424973.21      6956044.46
      1422733.64      6952763.22
#Sta/Elev= 30
  -727.6 1869.10  -137.4 1855.01   767.2 1848.17   825.4 1852.56   868.1 1848.87
  1129.3 1845.83  2630.8 1842.49  2682.5 1839.89  2753.1 1842.52  2790.0 1838.73
  2811.3 1840.89  3213.2 1838.56  4831.3 1844.19  4924.7 1841.18  4938.9 1837.97
  4975.8 1840.81  4983.9 1830.76  4986.1 1829.76  5010.9 1830.76  5012.7 1836.92
  5034.1 1838.86  5172.0 1842.73  6445.8 1846.38  6661.6 1842.98  7502.2 1842.12
  8459.4 1848.45  8848.2 1853.99  8884.1 1857.41  8899.0 1854.12  9018.3 1854.36
#Mann=3,-1,0
  -727.6    0.05       0  4983.9    0.05       0  5010.9    0.05       0
Bank Sta=4983.9,5010.9
Exp/Cntr=0.3,0.1

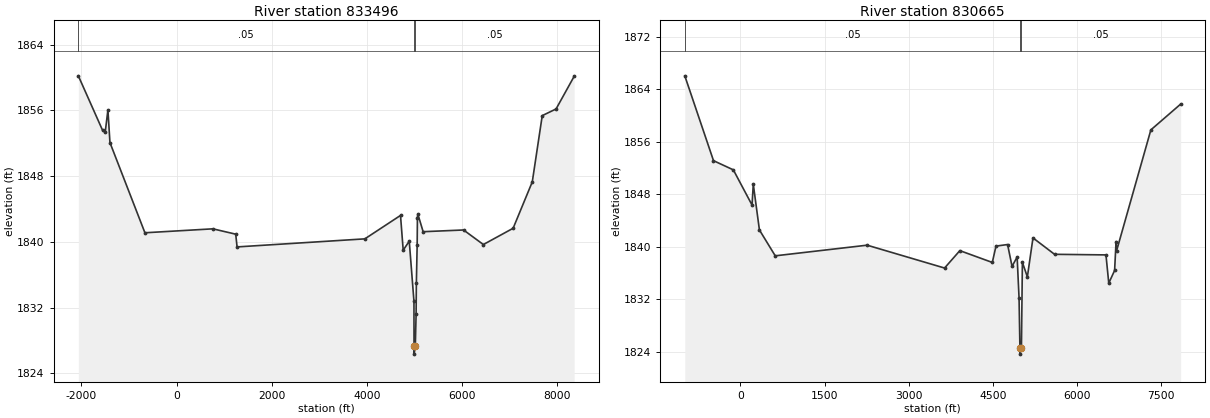
Type RM Length L Ch R = 1,833496,2831,2831,2831
BEGIN DESCRIPTION:
Clear Fork Brazos Rv 195.0
END DESCRIPTION:
XS GIS Cut Line= 3
      1431104.99      6959087.99      1426105.00      6954088.00
      1423104.97      6952587.98
#Sta/Elev= 30
 -2066.2 1860.19 -1557.1 1853.57 -1500.5 1853.36 -1444.0 1856.04 -1401.5 1852.07
  -666.1 1841.10   762.2 1841.58  1243.1 1840.93  1271.3 1839.38  3958.3 1840.36
  4707.9 1843.21  4764.4 1838.98  4891.7 1840.08  4990.7 1832.76  4992.1 1827.34
  4994.4 1826.34  5019.1 1827.34  5035.6 1831.16  5041.2 1834.96  5058.0 1839.60
  5063.6 1842.94  5071.9 1843.38  5183.7 1841.23  6033.5 1841.44  6449.9 1839.67
  7076.0 1841.65  7478.5 1847.29  7688.1 1855.35  7978.8 1856.16  8359.0 1860.13
#Mann=3,-1,0
 -2066.2    0.05       0  4992.1    0.05       0  5019.1    0.05       0
Bank Sta=4992.1,5019.1
Exp/Cntr=0.3,0.1

Type RM Length L Ch R = 1,830665,1895,1895,1895
BEGIN DESCRIPTION:
Clear Fork Brazos Rv 194.0
END DESCRIPTION:
XS GIS Cut Line= 3
      1431377.93      6959108.86      1428523.75      6953796.33
      1428655.00      6950988.00
#Sta/Elev= 30
  -992.5 1866.06  -480.7 1853.14  -126.8 1851.74   206.8 1846.38   228.7 1849.55
   338.3 1842.59   620.4 1838.65  2258.9 1840.27  3640.0 1836.79  3912.5 1839.44
  4491.3 1837.64  4557.0 1840.13  4763.9 1840.37  4843.3 1837.04  4934.1 1838.47
  4968.2 1832.24  4983.8 1824.68  4986.0 1823.68  5010.8 1824.68  5027.8 1837.66
  5116.6 1835.44  5216.7 1841.38  5601.3 1838.88  6518.1 1838.79  6568.2 1834.49
  6672.4 1836.42  6698.3 1840.82  6708.4 1839.44  7319.1 1857.83  7849.6 1861.75
#Mann=3,-1,0
  -992.5    0.05       0  4983.8    0.05       0  5010.8    0.05       0
Bank Sta=4983.8,5010.8
Exp/Cntr=0.3,0.1