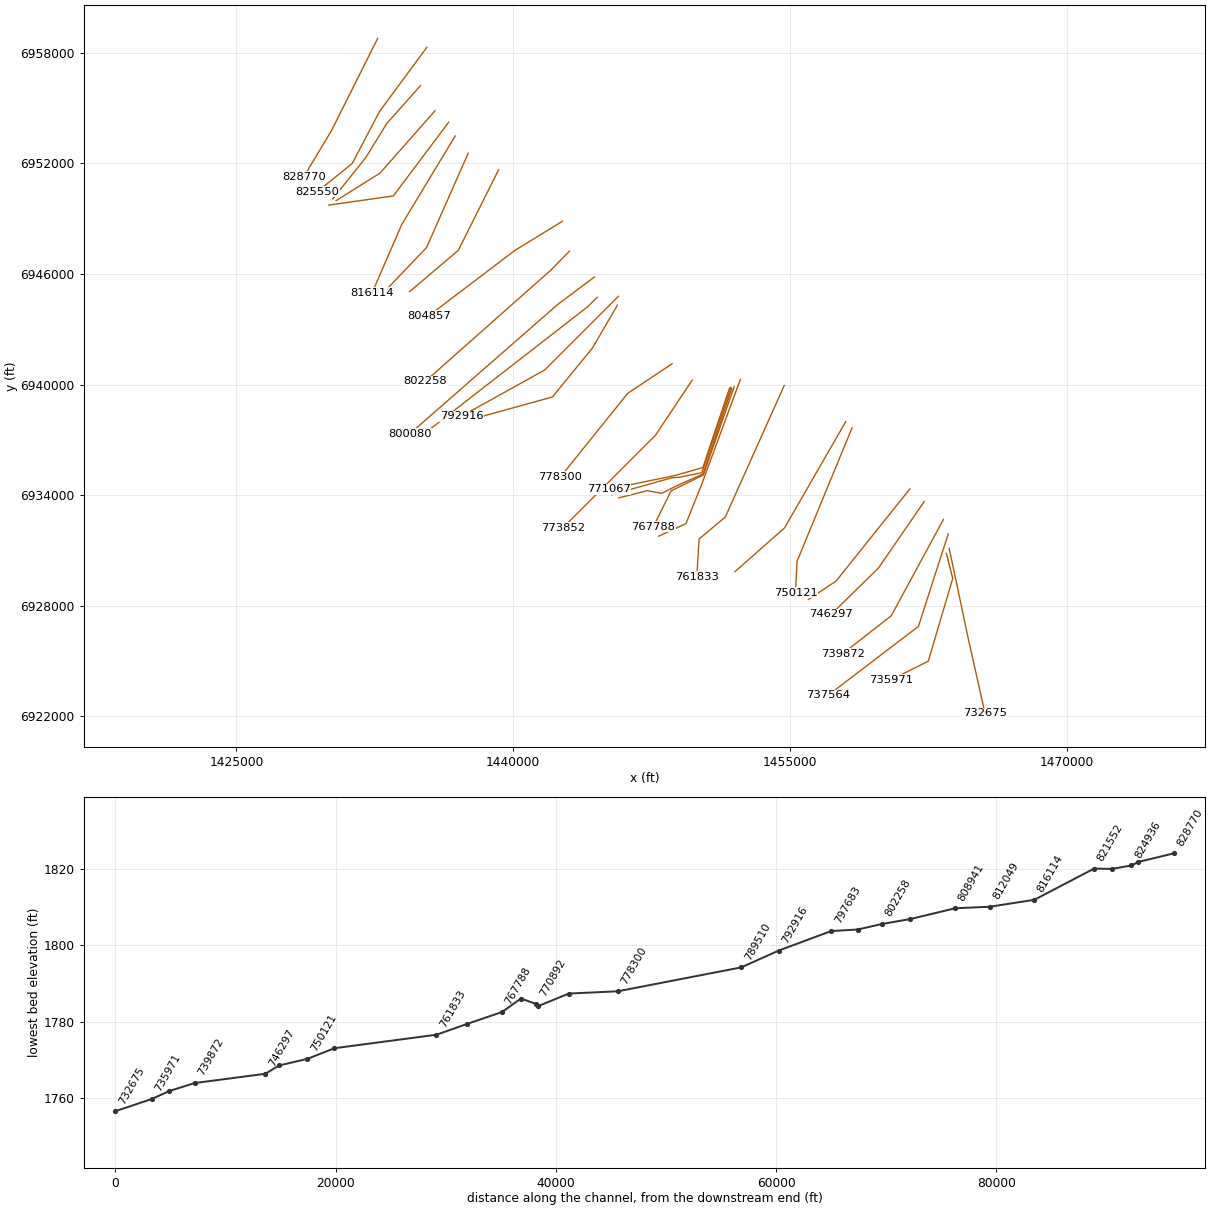
HEC-RAS study Clear Fork Brazos Rv.prj: Clear Fork Brazos Rv Base Level Engineering

--- Clear Fork Brazos Rv.g01 (geometry) --- (continued)

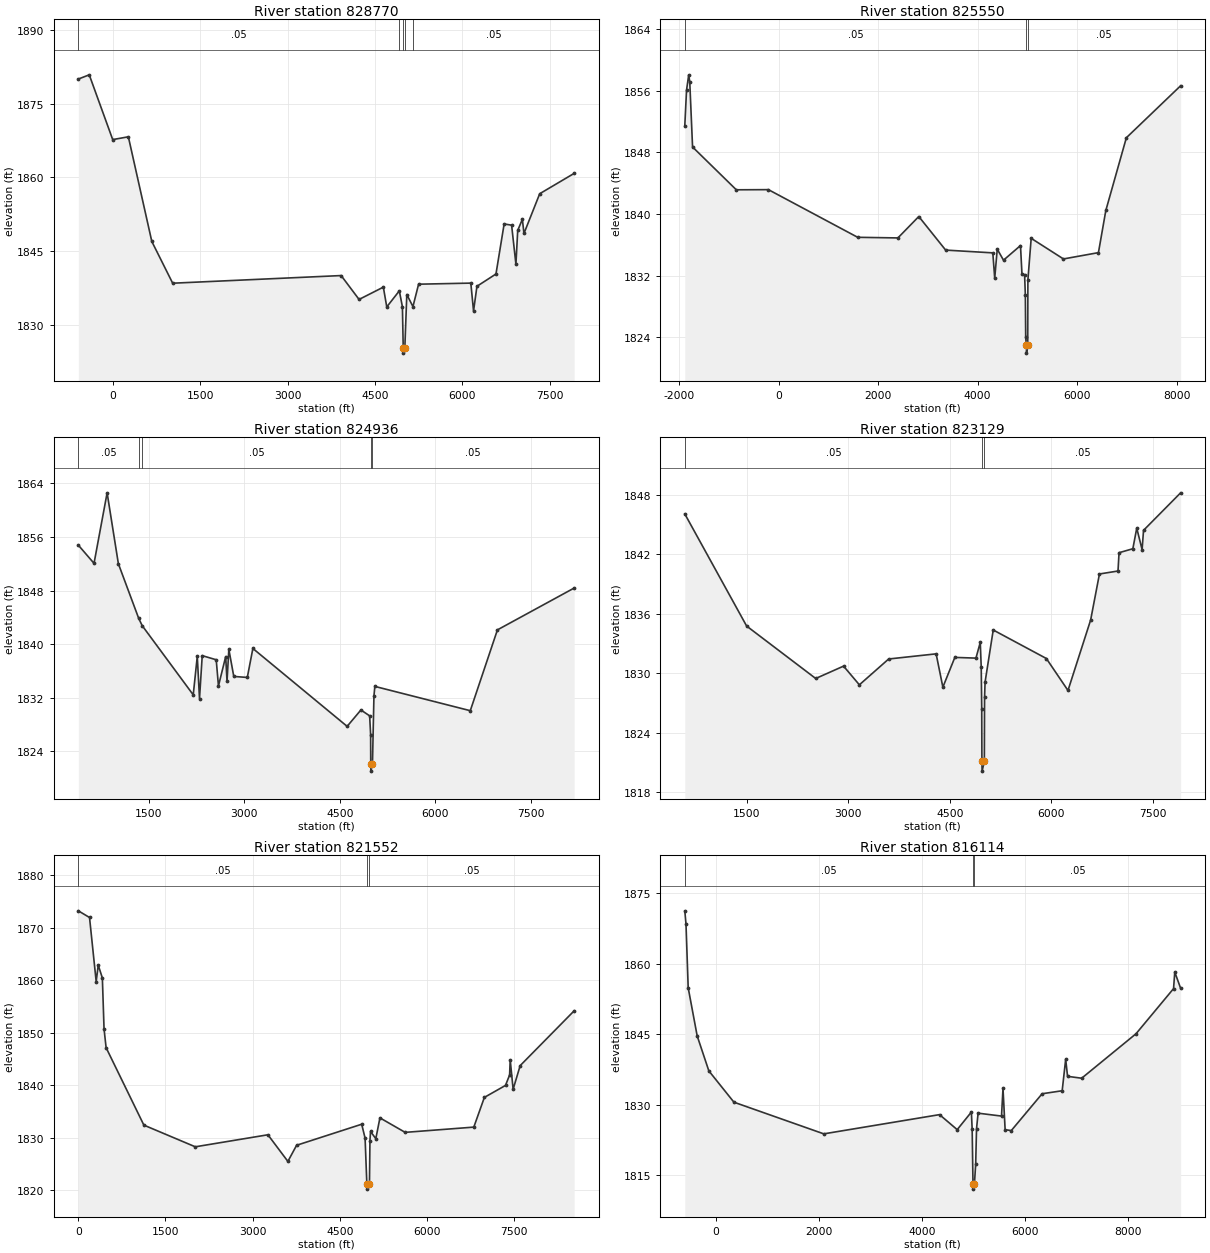
Type RM Length L Ch R = 1,828770,3220,3220,3220
BEGIN DESCRIPTION:
Clear Fork Brazos Rv 193.0
END DESCRIPTION:
XS GIS Cut Line= 3
      1432655.00      6958788.01      1430155.00      6953788.00
      1428654.98      6951287.96
#Sta/Elev= 30
  -589.4 1880.08  -402.1 1880.94     0.4 1867.73   268.7 1868.30   671.2 1846.95
  1029.0 1838.44  3919.1 1840.00  4226.5 1835.13  4643.0 1837.64  4701.7 1833.60
  4917.0 1836.88  4970.0 1833.64  4984.2 1825.18  4986.5 1824.18  5011.2 1825.18
  5045.5 1836.13  5150.8 1833.67  5247.6 1838.24  6143.6 1838.46  6190.3 1832.77
  6248.6 1837.81  6575.1 1840.32  6715.1 1850.52  6843.4 1850.28  6917.2 1842.31
  6948.3 1849.21  7028.0 1851.47  7055.2 1848.58  7325.4 1856.69  7916.3 1860.84
#Mann=5,-1,0
  -589.4    0.05       0  4917.0    0.12       0  4984.2    0.07       0
  5011.2    0.12       0  5150.8    0.05       0
Bank Sta=4984.2,5011.2
Exp/Cntr=0.3,0.1

Type RM Length L Ch R = 1,825550,614,614,614
BEGIN DESCRIPTION:
Mapping XS 6db7db48
END DESCRIPTION:
XS GIS Cut Line= 4
      1435320.45      6958301.42      1432750.99      6954811.82
      1431275.30      6951999.32      1429365.56      6950454.17
#Sta/Elev= 30
 -1884.6 1851.46 -1849.7 1856.07 -1805.8 1858.07 -1784.9 1857.15 -1728.6 1848.70
  -849.2 1843.14  -203.9 1843.16  1590.5 1836.97  2398.9 1836.89  2818.6 1839.67
  3358.7 1835.31  4306.5 1834.95  4344.9 1831.65  4395.6 1835.43  4521.4 1834.00
  4863.0 1835.90  4892.5 1832.21  4945.5 1832.12  4960.3 1829.51  4967.6 1823.98
  4981.3 1822.93  4983.6 1821.93  5008.3 1822.93  5011.7 1831.43  5077.8 1836.84
  5726.2 1834.16  6429.7 1834.98  6578.4 1840.46  6990.9 1849.90  8081.6 1856.65
#Mann=3,-1,0
 -1884.6    0.05       0  4981.3    0.05       0  5008.3    0.05       0
Bank Sta=4981.3,5008.3
Exp/Cntr=0.3,0.1

Type RM Length L Ch R = 1,824936,1807,1807,1807
BEGIN DESCRIPTION:
Mapping XS e73d3253
END DESCRIPTION:
XS GIS Cut Line= 4
      1434973.23      6956218.08      1433150.30      6954169.46
      1432004.46      6952311.82      1430216.55      6950072.59
#Sta/Elev= 30
   392.4 1854.78   639.0 1852.06   844.7 1862.60  1021.6 1852.00  1341.7 1843.82
  1396.5 1842.74  2197.7 1832.41  2261.2 1838.16  2296.3 1831.85  2339.0 1838.27
  2558.9 1837.65  2594.0 1833.74  2707.7 1838.13  2728.6 1834.43  2757.1 1839.22
  2834.8 1835.16  3047.2 1835.01  3134.7 1839.34  4615.9 1827.70  4832.3 1830.15
  4969.5 1829.27  4984.9 1826.44  4986.6 1822.01  4988.8 1821.01  5013.6 1822.01
  5037.0 1832.25  5051.5 1833.67  6550.6 1830.04  6977.2 1842.12  8182.7 1848.37
#Mann=5,-1,0
   392.4    0.05       0  1341.7    0.12       0  1396.5    0.05       0
  4986.6    0.03       0  5013.6    0.05       0
Bank Sta=4986.6,5013.6
Exp/Cntr=0.3,0.1

Type RM Length L Ch R = 1,823129,1577,1577,1577
BEGIN DESCRIPTION:
Mapping XS 6ec5b9ac
END DESCRIPTION:
XS GIS Cut Line= 3
      1435763.95      6954857.86      1432777.86      6951472.47
      1430399.66      6949979.58
#Sta/Elev= 30
   586.4 1846.09  1499.5 1834.76  2519.7 1829.46  2931.0 1830.71  3164.3 1828.82
  3596.9 1831.43  4297.9 1831.95  4397.5 1828.58  4574.0 1831.59  4886.1 1831.52
  4949.7 1833.11  4963.9 1830.61  4971.4 1826.37  4974.0 1821.10  4977.0 1820.10
  5010.0 1821.10  5013.2 1827.54  5020.8 1829.10  5141.2 1834.36  5925.8 1831.48
  6245.1 1828.25  6579.7 1835.37  6709.7 1840.02  6983.8 1840.32  6999.1 1842.17
  7202.9 1842.57  7260.6 1844.65  7339.6 1842.48  7360.8 1844.43  7908.5 1848.22
#Mann=3,-1,0
   586.4    0.05       0  4974.0    0.05       0  5010.0    0.05       0
Bank Sta=4974,5010
Exp/Cntr=0.3,0.1

Type RM Length L Ch R = 1,821552,5438,5438,5438
BEGIN DESCRIPTION:
Clear Fork Brazos Rv 190.0
END DESCRIPTION:
XS GIS Cut Line= 3
      1436505.02      6954238.02      1433505.00      6950238.00
      1430004.96      6949737.99
#Sta/Elev= 30
    -0.1 1873.20   192.6 1871.93   307.2 1859.74   342.6 1862.85   413.5 1860.42
   442.6 1850.71   478.1 1847.14  1128.1 1832.39  2013.5 1828.26  3263.5 1830.55
  3607.2 1825.48  3757.2 1828.55  4878.1 1832.56  4936.4 1829.91  4966.6 1821.20
  4970.3 1820.20  5011.6 1821.20  5020.1 1829.44  5030.2 1831.18  5121.1 1829.81
  5191.9 1833.77  5626.2 1831.01  6808.1 1832.01  6989.9 1837.67  7353.6 1839.95
  7424.3 1841.94  7434.4 1844.84  7484.9 1839.22  7606.1 1843.72  8535.5 1854.16
#Mann=3,-1,0
    -0.1    0.05       0  4966.6    0.05       0  5011.6    0.05       0
Bank Sta=4966.6,5011.6
Exp/Cntr=0.3,0.1

Type RM Length L Ch R = 1,816114,4065,4065,4065
BEGIN DESCRIPTION:
Clear Fork Brazos Rv 189.0
END DESCRIPTION:
XS GIS Cut Line= 3
      1436855.00      6953487.99      1433961.25      6948692.17
      1432354.98      6944987.96
#Sta/Elev= 30
  -609.6 1871.30  -586.3 1868.47  -543.6 1854.90  -368.9 1844.64  -142.4 1837.19
   345.4 1830.51  2092.4 1823.76  4342.4 1827.86  4685.7 1824.66  4961.5 1828.41
  4976.8 1824.70  4993.0 1812.98  4995.3 1811.98  5020.0 1812.98  5045.1 1817.30
  5061.6 1824.85  5092.1 1828.17  5547.2 1827.55  5576.1 1833.44  5617.5 1824.65
  5737.3 1824.46  6336.8 1832.31  6726.5 1832.95  6794.6 1839.66  6831.2 1836.02
  7105.7 1835.62  8162.2 1845.10  8891.8 1854.72  8915.3 1858.24  9029.1 1854.80
#Mann=3,-1,0
  -609.6    0.05       0  4993.0    0.05       0  5020.0    0.05       0
Bank Sta=4993,5020
Exp/Cntr=0.3,0.1

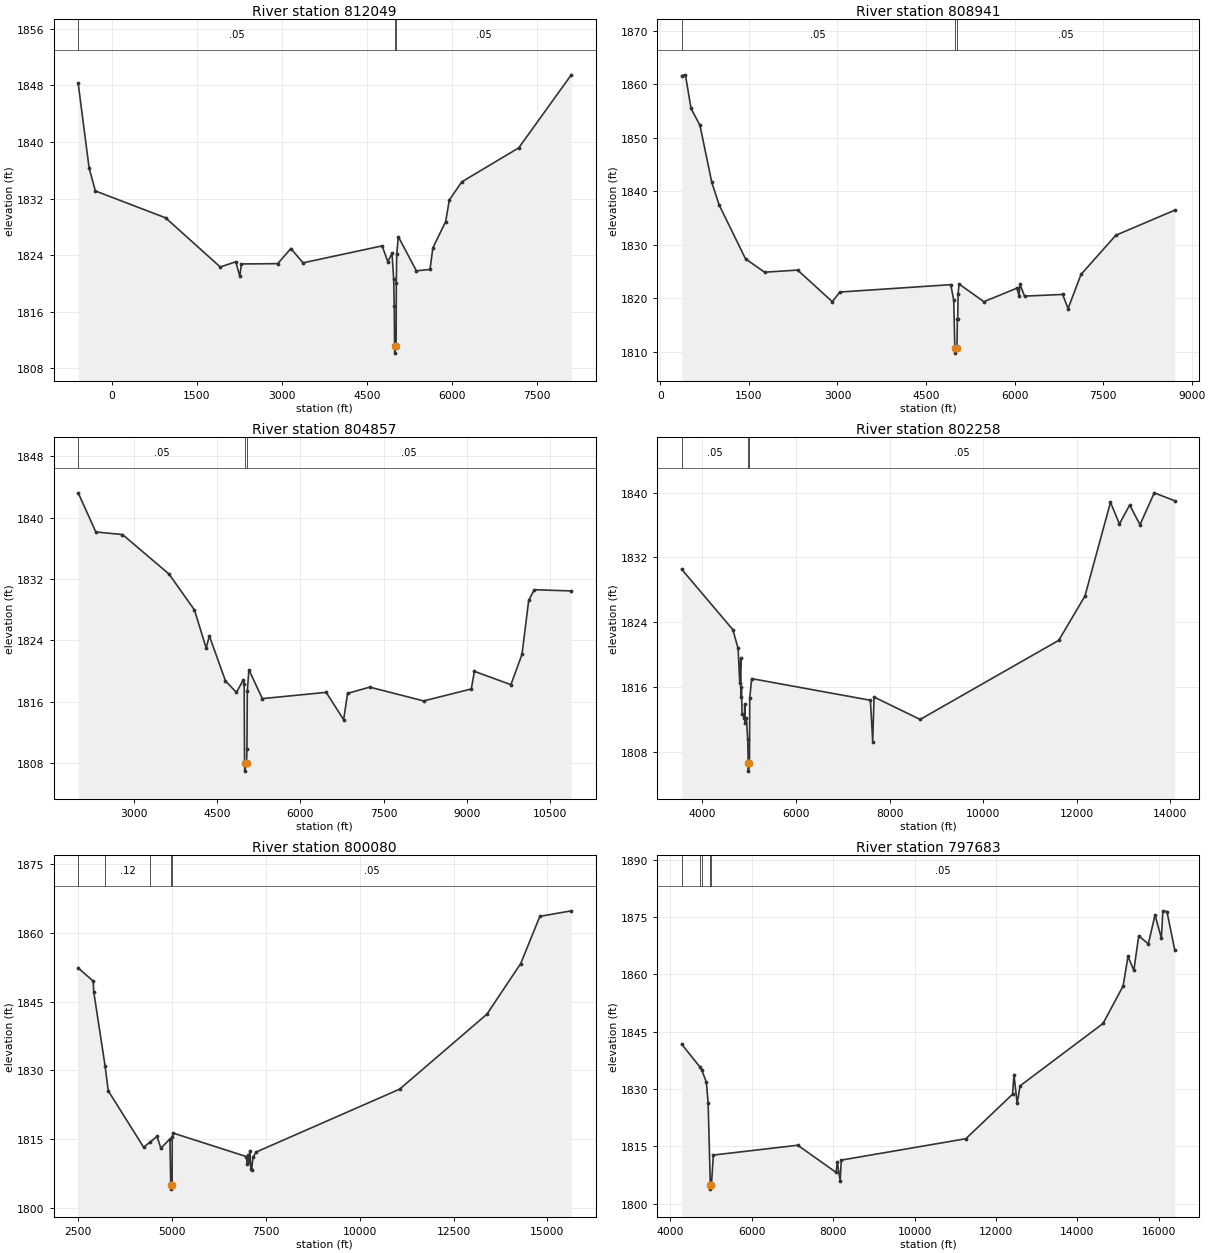
Type RM Length L Ch R = 1,812049,3108,3108,3108
BEGIN DESCRIPTION:
Clear Fork Brazos Rv 188.0
END DESCRIPTION:
XS GIS Cut Line= 3
      1437560.01      6952554.86      1435305.00      6947438.00
      1433168.82      6945194.98
#Sta/Elev= 30
  -591.6 1848.27  -398.5 1836.29  -288.8 1833.08   948.6 1829.28  1912.9 1822.33
  2185.9 1823.08  2255.9 1821.02  2284.7 1822.76  2923.8 1822.81  3155.7 1824.94
  3371.2 1822.92  4764.9 1825.32  4863.6 1823.10  4939.1 1824.24  4967.9 1820.61
  4978.3 1816.88  4983.9 1811.16  4986.1 1810.16  5010.9 1811.16  5014.1 1820.06
  5021.4 1824.11  5049.7 1826.62  5368.0 1821.79  5608.3 1821.99  5658.0 1825.03
  5884.1 1828.76  5948.0 1831.78  6167.2 1834.36  7171.5 1839.17  8097.6 1849.49
#Mann=3,-1,0
  -591.6    0.05       0  4983.9    0.05       0  5010.9    0.05       0
Bank Sta=4983.9,5010.9
Exp/Cntr=0.3,0.1

Type RM Length L Ch R = 1,808941,4084,4084,4084
BEGIN DESCRIPTION:
Mapping XS 9e3c1745
END DESCRIPTION:
XS GIS Cut Line= 3
      1439210.52      6951656.08      1437023.01      6947281.06
      1434385.00      6945042.23
#Sta/Elev= 30
   361.0 1861.60   424.8 1861.75   519.8 1855.47   670.8 1852.33   872.0 1841.65
   996.1 1837.45  1443.3 1827.37  1766.4 1824.89  2325.5 1825.28  2912.4 1819.38
  3041.0 1821.18  4919.3 1822.56  4969.6 1819.63  4987.7 1810.77  4990.7 1809.77
  5023.7 1810.77  5031.1 1816.15  5036.7 1816.22  5043.4 1820.85  5059.0 1822.68
  5480.3 1819.38  6040.5 1821.91  6076.1 1820.45  6089.9 1822.68  6167.9 1820.42
  6813.7 1820.73  6906.0 1818.10  7125.7 1824.48  7715.6 1831.79  8712.4 1836.47
#Mann=3,-1,0
   361.0    0.05       0  4987.7    0.05       0  5023.7    0.05       0
Bank Sta=4987.7,5023.7
Exp/Cntr=0.3,0.1

Type RM Length L Ch R = 1,804857,2599,2599,2599
BEGIN DESCRIPTION:
Clear Fork Brazos Rv 187.0
END DESCRIPTION:
XS GIS Cut Line= 3
      1442664.16      6948856.94      1440105.00      6947288.00
      1435424.58      6943735.41
#Sta/Elev= 30
  1997.6 1843.24  2315.2 1838.13  2794.8 1837.80  3632.2 1832.65  4090.5 1827.96
  4301.3 1823.00  4359.3 1824.57  4649.4 1818.70  4846.9 1817.20  4970.4 1818.84
  4985.8 1818.34  4993.0 1807.93  4996.0 1806.93  5029.0 1807.93  5035.8 1809.83
  5042.1 1817.36  5071.2 1820.15  5313.3 1816.39  6462.6 1817.21  6776.7 1813.64
  6847.4 1817.07  7246.8 1817.89  8218.0 1816.09  9074.9 1817.65  9131.1 1819.95
  9788.3 1818.21  9988.0 1822.16 10109.1 1829.22 10209.5 1830.60 10875.4 1830.44
#Mann=3,-1,0
  1997.6    0.05       0  4993.0    0.05       0  5029.0    0.05       0
Bank Sta=4993,5029
Exp/Cntr=0.3,0.1

Type RM Length L Ch R = 1,802258,2178,2178,2178
BEGIN DESCRIPTION:
Clear Fork Brazos Rv 186.0
END DESCRIPTION:
XS GIS Cut Line= 3
      1443044.57      6947233.82      1442044.58      6946213.00
      1435233.06      6940172.20
#Sta/Elev= 30
  3559.6 1830.55  4652.4 1823.09  4765.6 1820.77  4800.9 1816.49  4822.1 1819.55
  4829.1 1814.78  4836.3 1815.98  4850.4 1812.72  4899.9 1812.20  4907.0 1813.93
  4914.0 1811.53  4942.3 1812.23  4970.6 1809.58  4981.9 1806.62  4984.2 1805.62
  5008.9 1806.62  5013.4 1814.60  5055.2 1817.04  7591.8 1814.37  7641.2 1809.27
  7669.6 1814.77  8654.0 1812.00 11615.5 1821.77 12175.0 1827.24 12720.2 1838.81
 12911.8 1836.14 13130.9 1838.48 13350.8 1836.04 13655.3 1839.98 14092.9 1839.00
#Mann=3,-1,0
  3559.6    0.05       0  4981.9    0.05       0  5008.9    0.05       0
Bank Sta=4981.9,5008.9
Exp/Cntr=0.3,0.1

Type RM Length L Ch R = 1,800080,2397,2397,2397
BEGIN DESCRIPTION:
Clear Fork Brazos Rv 185.0
END DESCRIPTION:
XS GIS Cut Line= 3
      1444405.01      6945838.00      1442405.00      6944338.00
      1434404.96      6937337.97
#Sta/Elev= 30
  2505.4 1852.32  2905.4 1849.45  2918.9 1847.15  3220.9 1831.02  3305.4 1825.58
  4248.1 1813.30  4416.1 1814.40  4605.4 1815.64  4705.4 1813.10  4948.1 1815.09
  4968.9 1805.65  4979.7 1805.18  4981.9 1804.18  5006.7 1805.18  5008.7 1815.59
  5033.4 1816.38  6982.9 1811.27  7003.8 1809.69  7038.9 1811.60  7053.1 1810.00
  7075.0 1812.47  7103.4 1808.51  7124.3 1808.30  7159.4 1811.20  7251.5 1812.28
 11064.6 1825.94 13389.5 1842.26 14289.2 1853.28 14798.9 1863.55 15635.6 1864.75
#Mann=5,-1,0
  2505.4    0.05       0  3220.9    0.12       0  4416.1    0.05       0
  4979.7    0.05       0  5006.7    0.05       0
Bank Sta=4979.7,5006.7
Exp/Cntr=0.3,0.1

Type RM Length L Ch R = 1,797683,4767,4767,4767
BEGIN DESCRIPTION:
Clear Fork Brazos Rv 184.0
END DESCRIPTION:
XS GIS Cut Line= 3
      1444554.99      6944737.99      1444055.00      6944238.00
      1435054.96      6937237.97
#Sta/Elev= 30
  4280.5 1841.74  4735.2 1835.67  4775.2 1834.95  4888.6 1831.72  4931.0 1826.29
  4984.9 1804.88  4987.2 1803.78  5011.9 1804.88  5059.1 1812.70  7132.2 1815.27
  8073.3 1808.16  8102.3 1810.91  8172.8 1805.97  8201.8 1811.38 11258.6 1816.97
 12406.0 1828.61 12441.3 1833.77 12520.0 1826.20 12590.6 1830.81 14628.4 1847.13
 15121.6 1856.94 15241.9 1864.70 15384.9 1861.04 15505.3 1870.06 15741.4 1867.97
 15905.2 1875.54 16060.9 1869.46 16098.0 1876.62 16197.5 1876.44 16389.4 1866.42
#Mann=5,-1,0
  4280.5    0.05       0  4735.2    0.12       0  4775.2    0.05       0
  4984.9    0.05       0  5011.9    0.05       0
Bank Sta=4984.9,5011.9
Exp/Cntr=0.3,0.1

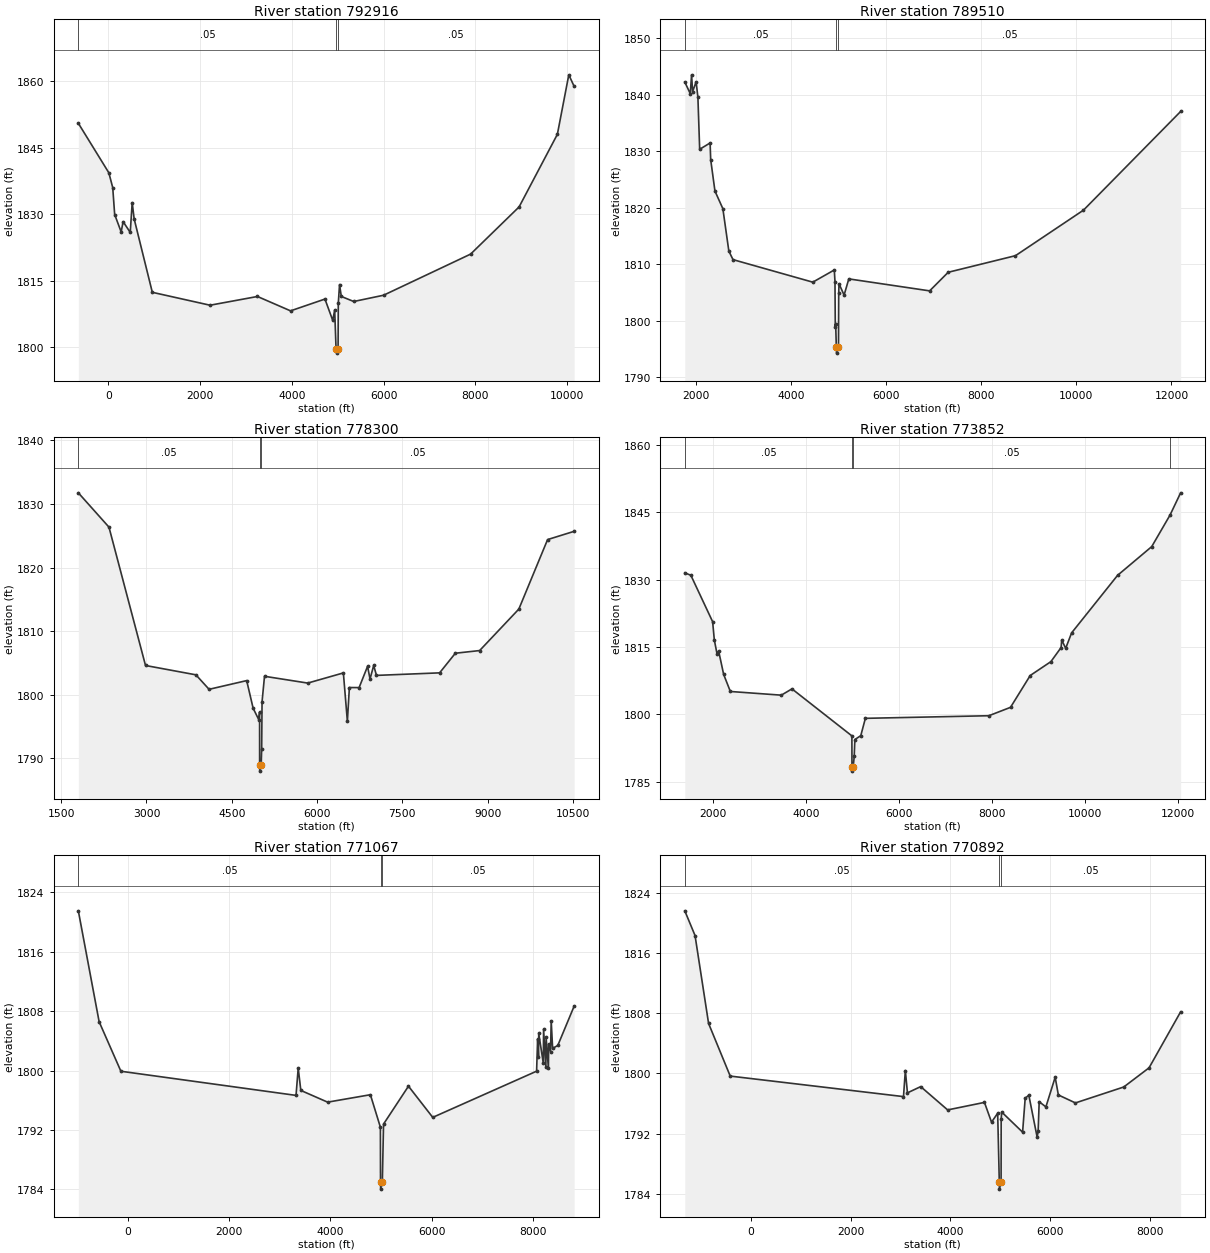
Type RM Length L Ch R = 1,792916,3406,3406,3406
BEGIN DESCRIPTION:
Clear Fork Brazos Rv 183.0
END DESCRIPTION:
XS GIS Cut Line= 3
      1445704.97      6944787.97      1441705.00      6940788.00
      1437205.03      6938288.02
#Sta/Elev= 30
  -651.1 1850.48    13.5 1839.32    98.4 1835.98   140.8 1829.91   282.2 1825.98
   324.7 1828.30   480.2 1825.87   522.7 1832.59   565.1 1828.94   961.1 1812.37
  2219.7 1809.46  3252.1 1811.43  3973.3 1808.19  4722.9 1810.85  4892.6 1806.04
  4935.0 1808.38  4963.3 1800.09  4973.0 1799.66  4976.0 1798.66  5009.0 1799.66
  5013.7 1809.89  5041.2 1814.12  5078.9 1811.44  5350.0 1810.30  5999.8 1811.71
  7896.5 1820.98  8953.5 1831.62  9787.5 1847.98 10036.8 1861.40 10153.5 1858.79
#Mann=3,-1,0
  -651.1    0.05       0  4973.0    0.05       0  5009.0    0.05       0
Bank Sta=4973,5009
Exp/Cntr=0.3,0.1

Type RM Length L Ch R = 1,789510,11210,11210,11210
BEGIN DESCRIPTION:
Mapping XS 0e8baea5
END DESCRIPTION:
XS GIS Cut Line= 4
      1445650.31      6944308.38      1444296.13      6941981.96
      1442125.99      6939325.71      1437978.32      6938180.33
#Sta/Elev= 30
  1769.1 1842.22  1884.2 1840.15  1911.5 1843.49  1933.0 1840.52  2007.5 1842.26
  2044.7 1839.49  2081.9 1830.31  2301.2 1831.43  2313.4 1828.48  2403.0 1822.92
  2569.3 1819.80  2695.2 1812.29  2782.7 1810.78  4460.3 1806.79  4912.4 1808.95
  4926.7 1806.90  4933.2 1798.90  4941.1 1799.39  4955.3 1795.23  4959.0 1794.23
  5000.3 1795.23  5005.0 1804.82  5011.4 1806.51  5118.4 1804.50  5217.5 1807.37
  6916.8 1805.25  7306.9 1808.54  8722.0 1811.48 10151.8 1819.54 12193.9 1837.00
#Mann=3,-1,0
  1769.1    0.05       0  4955.3    0.05       0  5000.3    0.05       0
Bank Sta=4955.3,5000.3
Exp/Cntr=0.3,0.1

Type RM Length L Ch R = 1,778300,4448,4448,4448
BEGIN DESCRIPTION:
Mapping XS 1c867b80
END DESCRIPTION:
XS GIS Cut Line= 3
      1448619.07      6941131.28      1446211.25      6939525.50
      1442560.01      6934985.41
#Sta/Elev= 30
  1801.3 1831.76  2340.0 1826.36  2982.9 1804.58  3869.2 1803.11  4100.6 1800.83
  4762.1 1802.20  4875.6 1797.85  4974.8 1796.05  4989.2 1797.26  4990.0 1788.85
  4992.2 1787.95  5017.0 1788.85  5025.9 1791.51  5032.4 1798.86  5075.6 1802.88
  5835.6 1801.81  6462.7 1803.41  6533.1 1795.80  6568.3 1801.11  6739.5 1801.10
  6888.3 1804.45  6931.5 1802.45  6995.5 1804.58  7045.1 1803.02  8155.3 1803.42
  8432.1 1806.51  8859.3 1806.93  9548.8 1813.46 10054.4 1824.40 10521.6 1825.70
#Mann=3,-1,0
  1801.3    0.05       0  4990.0    0.05       0  5017.0    0.05       0
Bank Sta=4990,5017
Exp/Cntr=0.3,0.1

Type RM Length L Ch R = 1,773852,2785,2785,2785
BEGIN DESCRIPTION:
Clear Fork Brazos Rv 178.0
END DESCRIPTION:
XS GIS Cut Line= 3
      1449704.97      6940237.96      1447705.00      6937238.00
      1442704.98      6932237.98
#Sta/Elev= 30
  1389.5 1831.52  1520.2 1830.97  1988.9 1820.63  2024.9 1816.59  2082.0 1813.55
  2118.1 1814.11  2226.2 1808.89  2370.5 1805.09  3467.2 1804.27  3697.0 1805.67
  4987.5 1795.20  4989.2 1788.35  4991.5 1787.35  5016.2 1788.35  5037.4 1790.62
  5051.6 1794.39  5178.9 1795.25  5277.8 1799.11  7936.6 1799.69  8403.3 1801.56
  8827.5 1808.65  9273.0 1811.74  9492.2 1814.88  9506.3 1816.55  9591.2 1814.71
  9718.5 1818.14 10708.4 1830.96 11443.8 1837.36 11838.8 1844.40 12066.1 1849.34
#Mann=4,-1,0
  1389.5    0.05       0  4989.2    0.05       0  5016.2    0.05       0
 11838.8    0.12       0
Bank Sta=4989.2,5016.2
Exp/Cntr=0.3,0.1

Type RM Length L Ch R = 1,771067,175,175,175
BEGIN DESCRIPTION:
Mapping XS 698f5e84
END DESCRIPTION:
XS GIS Cut Line= 4
      1451728.21      6939807.75      1450284.28      6935498.39
      1448742.09      6935057.77      1445168.08      6934320.95
#Sta/Elev= 30
  -981.3 1821.52  -570.3 1806.59  -140.1 1799.92  3320.6 1796.67  3363.6 1800.35
  3415.3 1797.34  3944.8 1795.76  4790.0 1796.76  4987.6 1792.39  4990.0 1785.05
  4993.0 1784.05  5026.0 1785.05  5050.0 1792.81  5542.5 1797.91  6022.1 1793.71
  8074.4 1799.93  8094.8 1804.26  8111.6 1801.86  8116.7 1805.01  8207.1 1801.00
  8212.2 1805.57  8257.4 1800.46  8262.5 1804.48  8307.6 1800.31  8312.8 1803.59
  8350.1 1802.58  8363.0 1806.71  8390.9 1803.00  8493.0 1803.39  8816.6 1808.69
#Mann=3,-1,0
  -981.3    0.05       0  4990.0   0.035       0  5026.0    0.05       0
Bank Sta=4990,5026
Exp/Cntr=0.3,0.1

Type RM Length L Ch R = 1,770892,1385,1385,1385
BEGIN DESCRIPTION:
Mapping XS d7e67f5c
END DESCRIPTION:
XS GIS Cut Line= 5
      1451804.85      6939851.58      1450224.96      6935218.77
      1448996.29      6934964.56      1448623.46      6934947.61
      1445335.74      6934024.00
#Sta/Elev= 30
 -1325.3 1821.64 -1119.9 1818.35  -848.4 1806.65  -415.0 1799.65  3058.0 1796.92
  3094.9 1800.39  3137.1 1797.42  3402.8 1798.25  3942.8 1795.15  4680.6 1796.15
  4822.3 1793.52  4945.6 1794.71  4978.0 1785.61  4981.0 1784.61  5014.0 1785.61
  5015.7 1793.90  5025.7 1794.87  5445.1 1792.19  5497.0 1796.70  5569.7 1797.11
  5736.6 1791.53  5756.7 1792.32  5777.5 1796.24  5912.1 1795.55  6098.1 1799.50
  6161.8 1797.14  6504.0 1796.08  7472.8 1798.20  7979.6 1800.75  8612.4 1808.20
#Mann=3,-1,0
 -1325.3    0.05       0  4978.0    0.03       0  5014.0    0.05       0
Bank Sta=4978,5014
Exp/Cntr=0.3,0.1

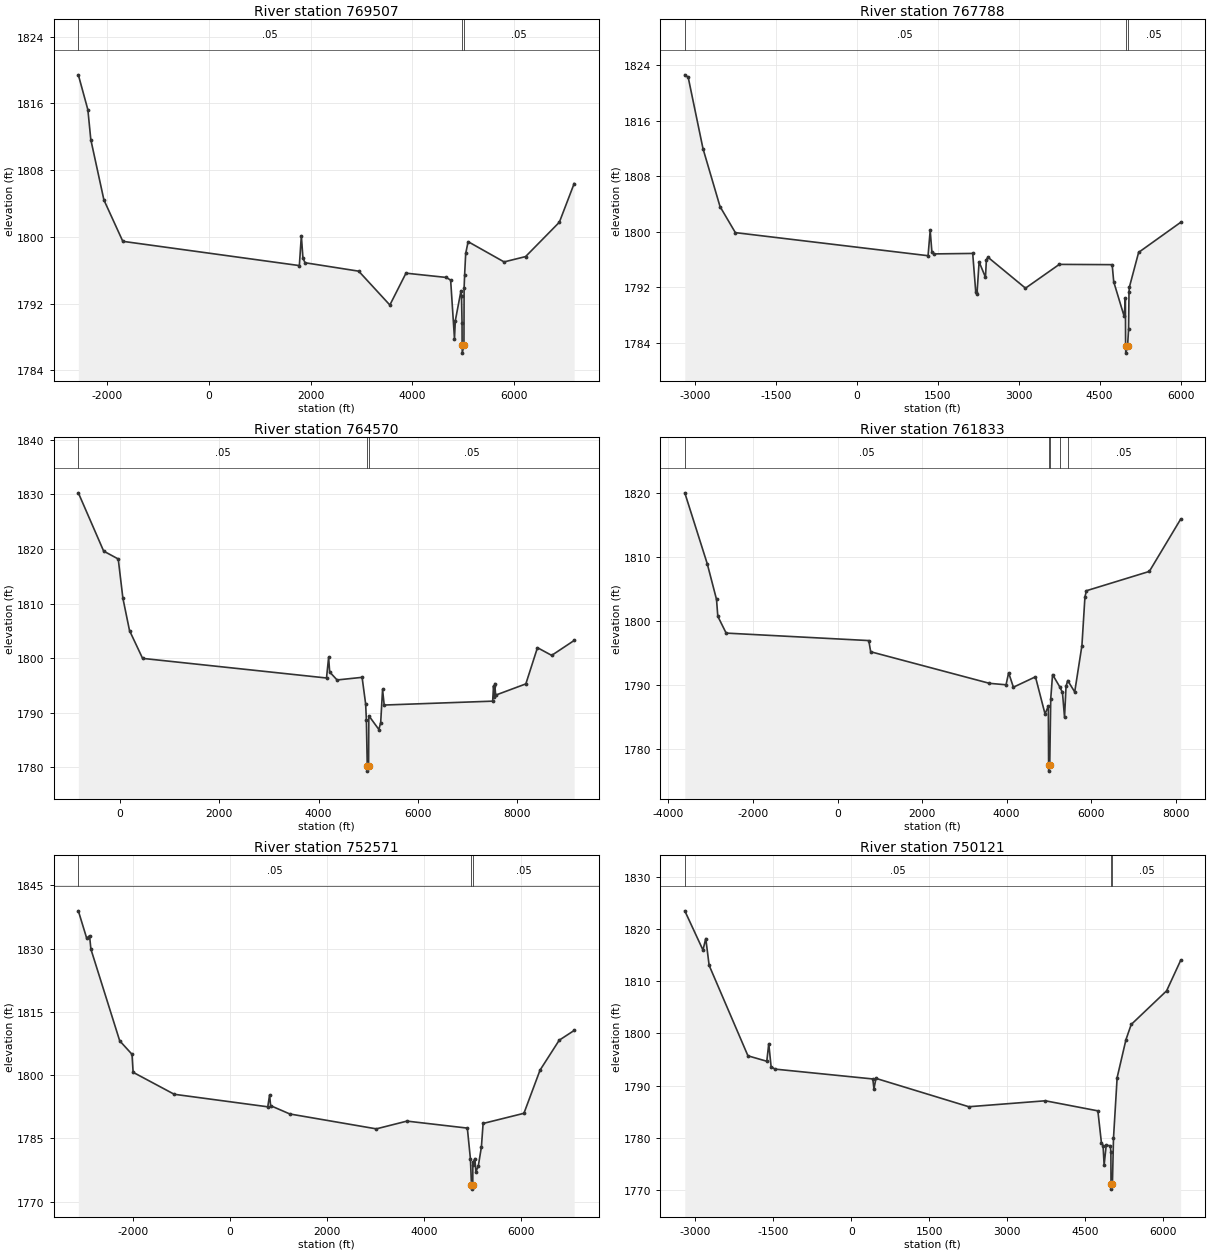
Type RM Length L Ch R = 1,769507,1719,1719,1719
BEGIN DESCRIPTION:
Mapping XS 289047ad
END DESCRIPTION:
XS GIS Cut Line= 6
      1451848.63      6939774.90      1450285.63      6935139.99
      1448849.85      6934503.68      1448050.38      6934095.79
      1447267.22      6934242.63      1445718.61      6933851.40
#Sta/Elev= 30
 -2567.4 1819.43 -2379.7 1815.24 -2322.0 1811.66 -2064.1 1804.42 -1692.5 1799.46
  1780.4 1796.55  1819.5 1800.14  1851.2 1797.43  1893.4 1796.89  2948.1 1795.88
  3560.6 1791.82  3877.8 1795.64  4667.5 1795.13  4756.4 1794.81  4832.0 1787.77
  4848.3 1789.94  4960.2 1793.54  4970.4 1792.92  4980.5 1789.64  4982.0 1787.05
  4985.0 1786.05  5018.0 1787.05  5021.2 1793.84  5031.4 1795.44  5052.5 1798.00
  5100.0 1799.42  5807.6 1796.99  6230.5 1797.63  6894.7 1801.75  7186.0 1806.39
#Mann=3,-1,0
 -2567.4    0.05       0  4982.0   0.035       0  5018.0    0.05       0
Bank Sta=4982,5018
Exp/Cntr=0.3,0.1

Type RM Length L Ch R = 1,767788,3218,3218,3218
BEGIN DESCRIPTION:
Mapping XS 7c27397e
END DESCRIPTION:
XS GIS Cut Line= 4
      1451980.00      6939884.39      1450305.94      6935089.91
      1448555.51      6934228.15      1447604.00      6932289.25
#Sta/Elev= 30
 -3187.7 1822.64 -3124.8 1822.29 -2850.6 1812.00 -2534.8 1803.64 -2250.7 1799.88
  1320.7 1796.55  1360.2 1800.21  1391.2 1797.14  1427.6 1796.81  2148.1 1796.88
  2205.0 1791.26  2227.4 1791.06  2266.8 1795.66  2384.7 1793.44  2401.6 1795.97
  2429.6 1796.34  3126.1 1791.87  3753.1 1795.30  4733.0 1795.26  4761.5 1792.79
  4955.8 1787.79  4978.1 1790.44  4982.0 1783.50  4985.0 1782.50  5018.0 1783.50
  5036.9 1785.96  5044.9 1791.36  5053.9 1792.08  5223.1 1797.03  6001.5 1801.36
#Mann=3,-1,0
 -3187.7    0.05       0  4982.0    0.05       0  5018.0    0.05       0
Bank Sta=4982,5018
Exp/Cntr=0.3,0.1

Type RM Length L Ch R = 1,764570,2737,2737,2737
BEGIN DESCRIPTION:
Mapping XS 25627341
END DESCRIPTION:
XS GIS Cut Line= 4
      1452316.96      6940280.57      1450198.91      6934534.04
      1449365.58      6932450.71      1447889.94      6931773.65
#Sta/Elev= 30
  -841.8 1830.28  -331.5 1819.61   -37.7 1818.17    56.2 1810.98   189.9 1805.06
   453.2 1799.97  4159.4 1796.38  4202.0 1800.15  4223.3 1797.48  4372.5 1796.02
  4876.7 1796.50  4948.0 1791.63  4962.7 1788.72  4980.5 1780.33  4982.8 1779.33
  5007.5 1780.33  5012.0 1789.48  5214.5 1786.95  5251.2 1788.22  5289.1 1794.28
  5321.5 1791.43  7507.8 1792.14  7525.2 1794.94  7544.3 1792.87  7549.8 1795.37
  7567.3 1793.24  8176.2 1795.30  8410.5 1801.93  8697.4 1800.52  9150.0 1803.25
#Mann=3,-1,0
  -841.8    0.05       0  4980.5    0.04       0  5007.5    0.05       0
Bank Sta=4980.5,5007.5
Exp/Cntr=0.3,0.1

Type RM Length L Ch R = 1,761833,9262,9262,9262
BEGIN DESCRIPTION:
Mapping XS d492d32d
END DESCRIPTION:
XS GIS Cut Line= 4
      1454695.44      6939950.72      1451500.99      6932815.29
      1450077.38      6931617.38      1449955.85      6929568.79
#Sta/Elev= 30
 -3614.3 1820.08 -3083.5 1808.99 -2863.8 1803.40 -2833.4 1800.76 -2636.2 1798.13
   738.4 1796.96   783.7 1795.21  3593.3 1790.27  3986.3 1790.04  4047.2 1791.93
  4159.6 1789.66  4681.9 1791.29  4908.3 1785.48  4986.4 1786.71  4993.0 1777.53
  4995.3 1776.53  5020.0 1777.53  5043.6 1787.86  5086.5 1791.64  5253.0 1789.76
  5320.6 1788.84  5370.0 1784.94  5405.1 1789.78  5444.9 1790.71  5610.6 1788.92
  5781.0 1796.17  5852.5 1803.78  5887.7 1804.76  7375.8 1807.78  8116.3 1815.95
#Mann=5,-1,0
 -3614.3    0.05       0  4993.0    0.05       0  5020.0    0.05       0
  5253.0    0.12       0  5444.9    0.05       0
Bank Sta=4993,5020
Exp/Cntr=0.3,0.1

Type RM Length L Ch R = 1,752571,2450,2450,2450
BEGIN DESCRIPTION:
Mapping XS 3b9d22b6
END DESCRIPTION:
XS GIS Cut Line= 3
      1458028.79      6937988.93      1454712.80      6932225.01
      1452021.86      6929846.57
#Sta/Elev= 30
 -3133.7 1838.98 -2960.5 1832.46 -2901.9 1833.08 -2874.2 1829.90 -2279.3 1808.16
 -2025.1 1804.96 -2002.0 1800.69 -1152.5 1795.48   779.2 1792.51   816.6 1795.32
   838.1 1792.78  1234.8 1790.81  3021.3 1787.28  3654.1 1789.12  4901.1 1787.46
  4964.9 1780.14  4986.5 1773.99  4988.8 1772.99  5013.5 1773.99  5014.2 1778.82
  5021.2 1779.35  5056.9 1780.24  5077.8 1777.07  5128.0 1778.51  5191.6 1782.99
  5226.7 1788.56  6069.9 1790.97  6402.8 1801.21  6799.3 1808.31  7107.4 1810.61
#Mann=3,-1,0
 -3133.7    0.05       0  4986.5    0.05       0  5013.5    0.05       0
Bank Sta=4986.5,5013.5
Exp/Cntr=0.3,0.1

Type RM Length L Ch R = 1,750121,2580,2580,2580
BEGIN DESCRIPTION:
Clear Fork Brazos Rv 174.0
END DESCRIPTION:
XS GIS Cut Line= 3
      1458370.32      6937650.89      1455389.68      6930412.19
      1455300.97      6928708.94
#Sta/Elev= 30
 -3202.7 1823.49 -2853.5 1815.98 -2799.4 1818.19 -2734.6 1813.04 -1988.3 1795.72
 -1626.0 1794.68 -1588.2 1798.05 -1543.4 1793.67 -1471.5 1793.18   412.5 1791.29
   434.1 1789.40   473.5 1791.40  2258.7 1785.97  3729.5 1787.11  4740.0 1785.18
  4808.4 1779.05  4840.1 1778.54  4860.2 1774.77  4900.2 1778.58  4980.3 1778.50
  4990.3 1777.26  4992.6 1771.19  4994.9 1770.19  5019.6 1771.19  5040.4 1779.95
  5110.5 1791.55  5280.7 1798.84  5380.9 1801.72  6061.8 1808.17  6331.2 1813.99
#Mann=3,-1,0
 -3202.7    0.05       0  4992.6    0.05       0  5019.6    0.05       0
Bank Sta=4992.6,5019.6
Exp/Cntr=0.3,0.1

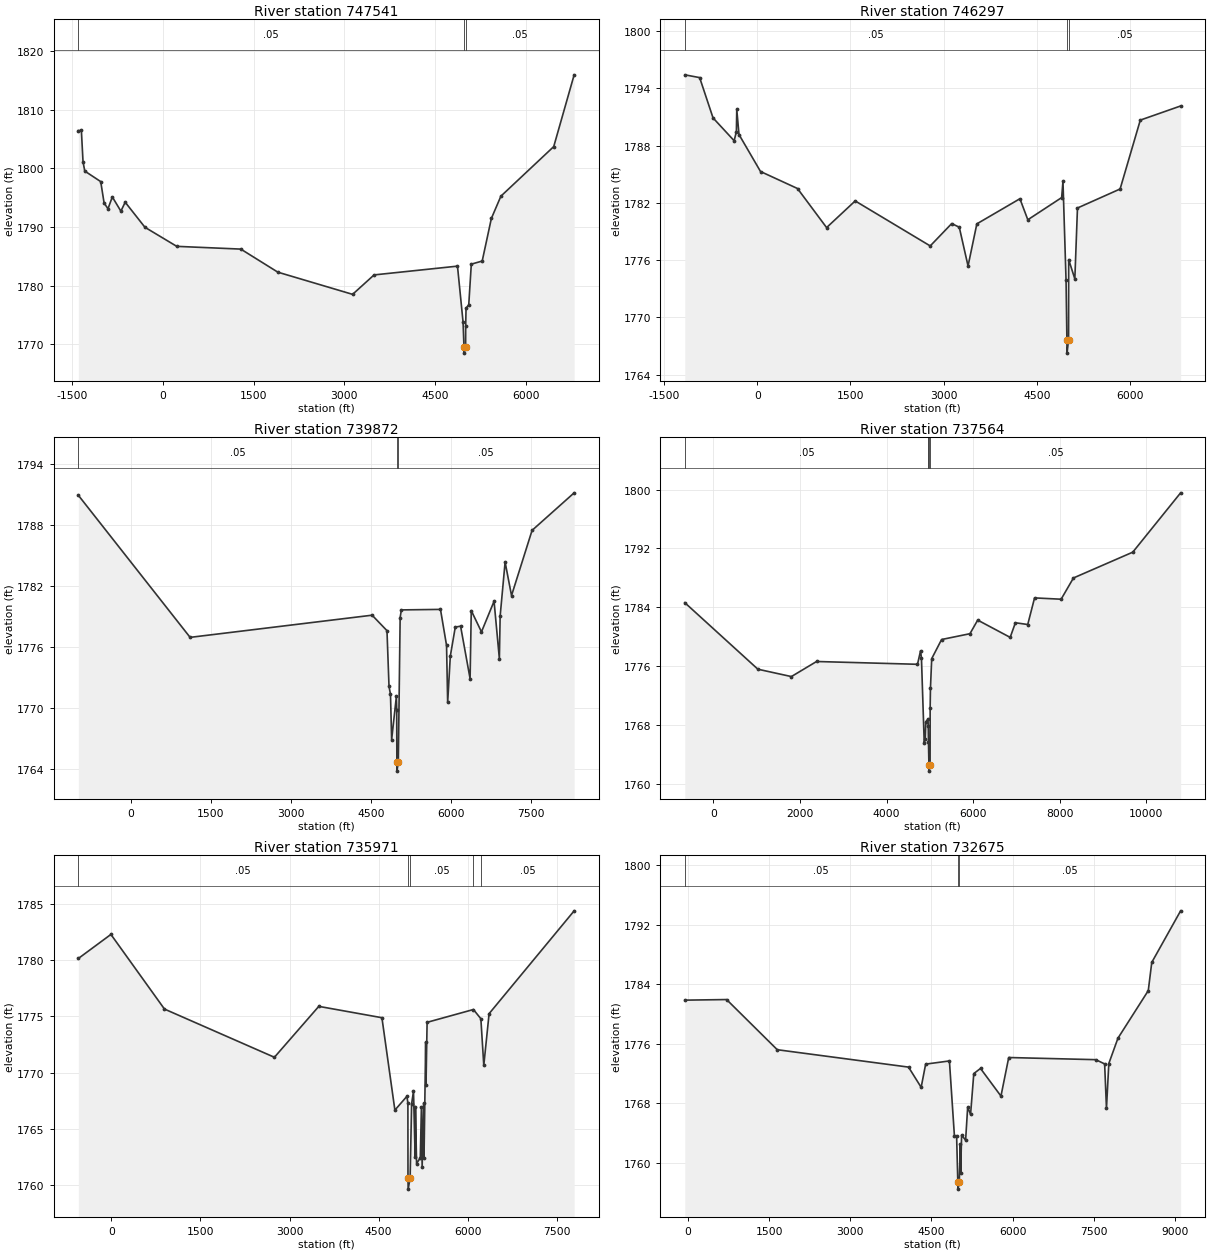
Type RM Length L Ch R = 1,747541,1244,1244,1244
BEGIN DESCRIPTION:
Clear Fork Brazos Rv 173.0
END DESCRIPTION:
XS GIS Cut Line= 3
      1461504.97      6934337.97      1457505.00      6929338.00
      1456004.97      6928337.98
#Sta/Elev= 30
 -1402.6 1806.46 -1352.2 1806.48 -1325.0 1801.15 -1296.2 1799.55 -1032.1 1797.75
  -976.0 1794.09  -912.0 1793.11  -840.0 1795.13  -698.3 1792.70  -627.1 1794.23
  -300.5 1789.95   226.2 1786.69  1286.7 1786.22  1899.0 1782.28  3136.4 1778.49
  3491.7 1781.81  4872.4 1783.31  4964.5 1773.78  4980.2 1769.45  4982.4 1768.45
  5007.2 1769.45  5008.0 1773.10  5014.0 1776.11  5059.1 1776.74  5101.1 1783.65
  5281.4 1784.18  5433.2 1791.46  5590.9 1795.26  6465.2 1803.73  6803.3 1815.99
#Mann=3,-1,0
 -1402.6    0.05       0  4980.2    0.05       0  5007.2    0.05       0
Bank Sta=4980.2,5007.2
Exp/Cntr=0.3,0.1

Type RM Length L Ch R = 1,746297,6425,6425,6425
BEGIN DESCRIPTION:
Mapping XS 99c61be0
END DESCRIPTION:
XS GIS Cut Line= 3
      1462283.45      6933652.62      1459800.79      6930041.48
      1457231.37      6927524.14
#Sta/Elev= 30
 -1165.3 1795.40  -926.4 1795.11  -710.7 1790.89  -370.9 1788.50  -335.1 1789.46
  -329.0 1791.78  -293.2 1789.15    53.3 1785.28   648.5 1783.50  1116.7 1779.41
  1576.8 1782.20  2784.3 1777.49  3130.1 1779.83  3251.8 1779.45  3393.1 1775.39
  3534.6 1779.80  4227.6 1782.43  4354.9 1780.23  4899.4 1782.55  4920.6 1784.25
  4970.2 1773.88  4983.9 1767.67  4986.1 1766.27  5010.9 1767.67  5012.6 1776.06
  5111.6 1774.04  5154.0 1781.46  5840.0 1783.45  6165.1 1790.66  6814.0 1792.14
#Mann=3,-1,0
 -1165.3    0.05       0  4983.9   0.035       0  5010.9    0.05       0
Bank Sta=4983.9,5010.9
Exp/Cntr=0.3,0.1

Type RM Length L Ch R = 1,739872,2308,2308,2308
BEGIN DESCRIPTION:
Mapping XS 7518104d
END DESCRIPTION:
XS GIS Cut Line= 3
      1463325.08      6932680.34      1460495.23      6927454.68
      1457856.35      6925388.71
#Sta/Elev= 30
  -982.6 1790.95  1112.6 1776.98  4524.2 1779.16  4802.9 1777.64  4841.0 1772.16
  4868.6 1771.38  4890.4 1766.93  4979.2 1771.18  4985.8 1769.83  4988.0 1764.73
  4990.3 1763.83  5015.0 1764.73  5049.8 1778.93  5072.4 1779.68  5805.7 1779.73
  5919.6 1776.19  5940.4 1770.58  5990.1 1775.14  6083.2 1777.99  6182.7 1778.08
  6360.8 1772.92  6382.8 1779.61  6574.2 1777.52  6810.2 1780.53  6909.7 1774.88
  6924.1 1779.07  7017.2 1784.38  7137.5 1781.09  7522.7 1787.50  8311.5 1791.19
#Mann=3,-1,0
  -982.6    0.05       0  4988.0    0.05       0  5015.0    0.05       0
Bank Sta=4988,5015
Exp/Cntr=0.3,0.1

Type RM Length L Ch R = 1,737564,1593,1593,1593
BEGIN DESCRIPTION:
Mapping XS ab1d7112
END DESCRIPTION:
XS GIS Cut Line= 3
      1463584.33      6931895.16      1461969.74      6926877.79
      1457056.57      6923127.81
#Sta/Elev= 30
  -661.8 1784.63  1026.5 1775.58  1799.7 1774.58  2381.7 1776.63  4712.5 1776.25
  4783.2 1778.08  4804.0 1777.07  4868.4 1765.51  4891.2 1766.15  4904.3 1768.43
  4952.4 1768.78  4961.9 1767.80  4965.9 1765.71  4976.5 1762.62  4978.7 1761.72
  5003.5 1762.62  5004.9 1770.29  5011.8 1773.00  5040.9 1777.02  5269.1 1779.62
  5924.2 1780.41  6102.9 1782.26  6853.1 1779.91  6973.7 1781.90  7258.5 1781.66
  7416.4 1785.28  8029.5 1785.10  8314.3 1787.99  9684.6 1791.50 10789.7 1799.57
#Mann=5,-1,0
  -661.8    0.05       0  4952.4    0.12       0  4965.9    0.05       0
  4976.5    0.05       0  5003.5    0.05       0
Bank Sta=4976.5,5003.5
Exp/Cntr=0.3,0.1

Type RM Length L Ch R = 1,735971,3296,3296,3296
BEGIN DESCRIPTION:
Mapping XS de2d1ca5
END DESCRIPTION:
XS GIS Cut Line= 4
      1463485.04      6930832.65      1463827.67      6929478.44
      1462506.10      6924991.62      1460478.43      6923970.62
#Sta/Elev= 30
  -553.9 1780.15    -5.6 1782.29   895.6 1775.65  2746.0 1771.36  3492.9 1775.89
  4555.4 1774.88  4773.6 1766.66  4976.3 1767.89  4992.5 1767.28  4994.0 1760.63
  4997.0 1759.63  5030.0 1760.63  5055.0 1767.22  5086.7 1768.34  5114.8 1762.50
  5120.0 1766.97  5138.4 1761.90  5201.0 1762.42  5220.0 1766.95  5232.3 1761.61
  5258.6 1767.25  5263.8 1762.42  5291.9 1772.71  5297.1 1768.87  5315.7 1774.47
  6095.3 1775.61  6220.5 1774.79  6269.7 1770.64  6359.0 1775.24  7790.6 1784.39
#Mann=5,-1,0
  -553.9    0.05       0  4994.0    0.05       0  5030.0    0.05       0
  6095.3    0.12       0  6220.5    0.05       0
Bank Sta=4994,5030
Exp/Cntr=0.3,0.1

Type RM Length L Ch R = 1,732675,481,481,481
BEGIN DESCRIPTION:
Clear Fork Brazos Rv 169.0
END DESCRIPTION:
XS GIS Cut Line= 3
      1463636.41      6931113.88      1464680.66      6926169.23
      1465580.42      6922157.50
#Sta/Elev= 30
   -57.7 1781.86   714.9 1781.94  1651.8 1775.19  4077.9 1772.85  4311.3 1770.13
  4394.3 1773.25  4833.7 1773.68  4925.7 1763.63  4966.6 1763.62  4988.8 1757.43
  4991.0 1756.43  5015.8 1757.43  5035.9 1762.47  5041.0 1758.54  5058.8 1763.70
  5132.9 1763.02  5171.1 1767.46  5224.7 1766.49  5284.2 1771.98  5408.3 1772.67
  5786.4 1768.95  5929.9 1774.14  7538.9 1773.85  7702.9 1773.28  7736.7 1767.28
  7780.0 1773.33  7948.8 1776.74  8509.4 1783.14  8574.0 1786.94  9107.4 1793.88
#Mann=3,-1,0
   -57.7    0.05       0  4988.8    0.05       0  5015.8    0.05       0
Bank Sta=4988.8,5015.8
Exp/Cntr=0.3,0.1