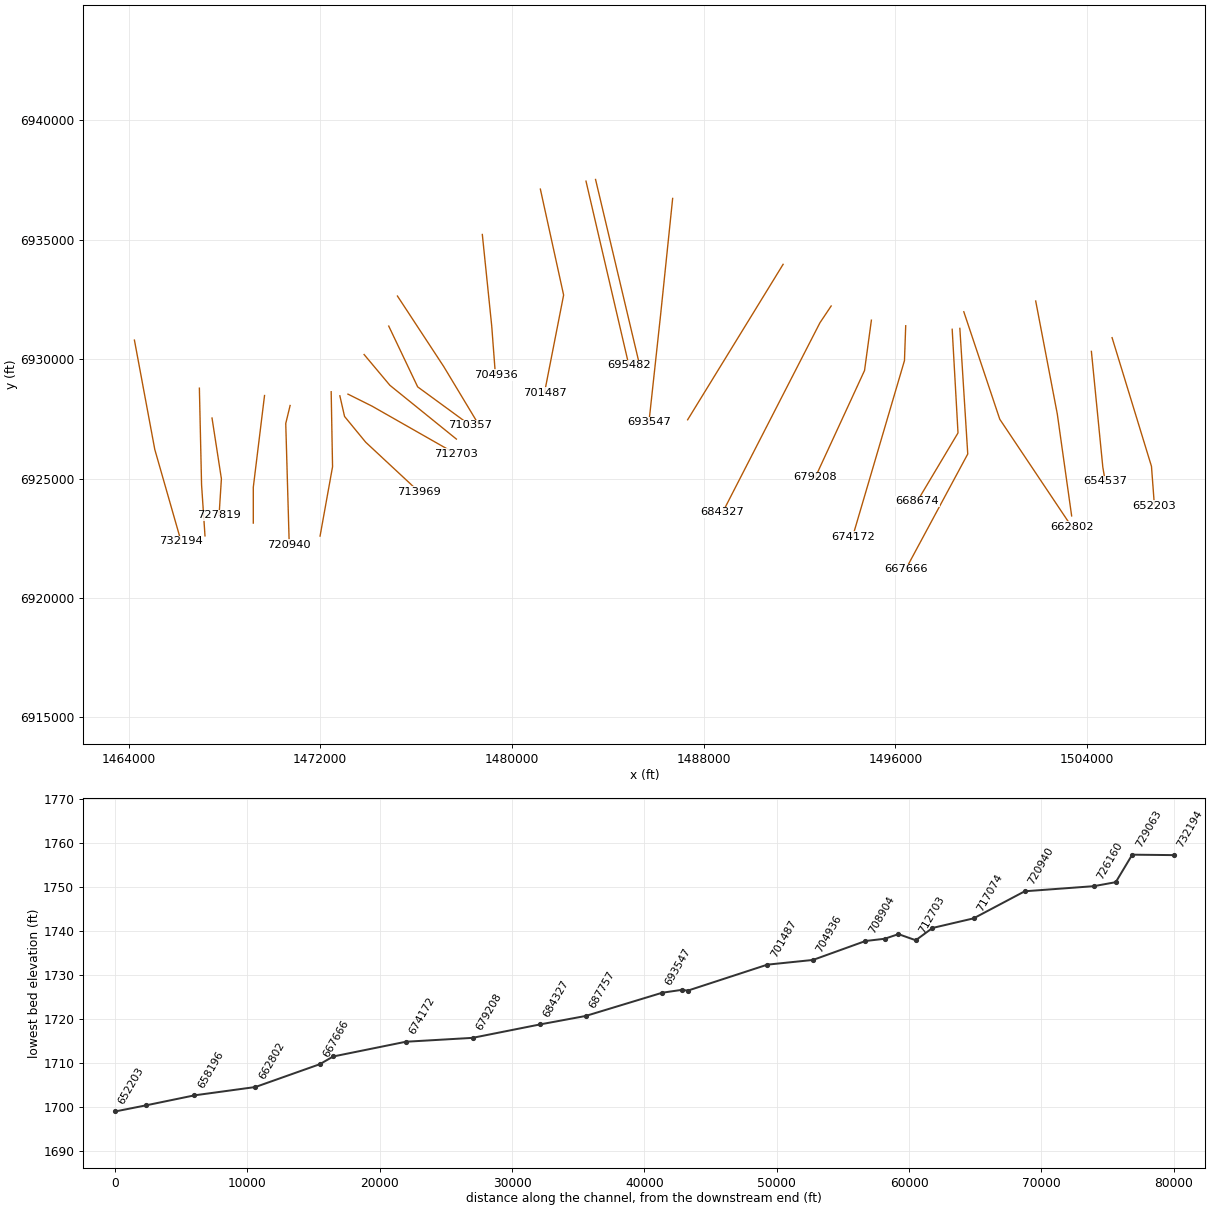
HEC-RAS study Clear Fork Brazos Rv.prj: Clear Fork Brazos Rv Base Level Engineering

--- Clear Fork Brazos Rv.g01 (geometry) --- (continued)

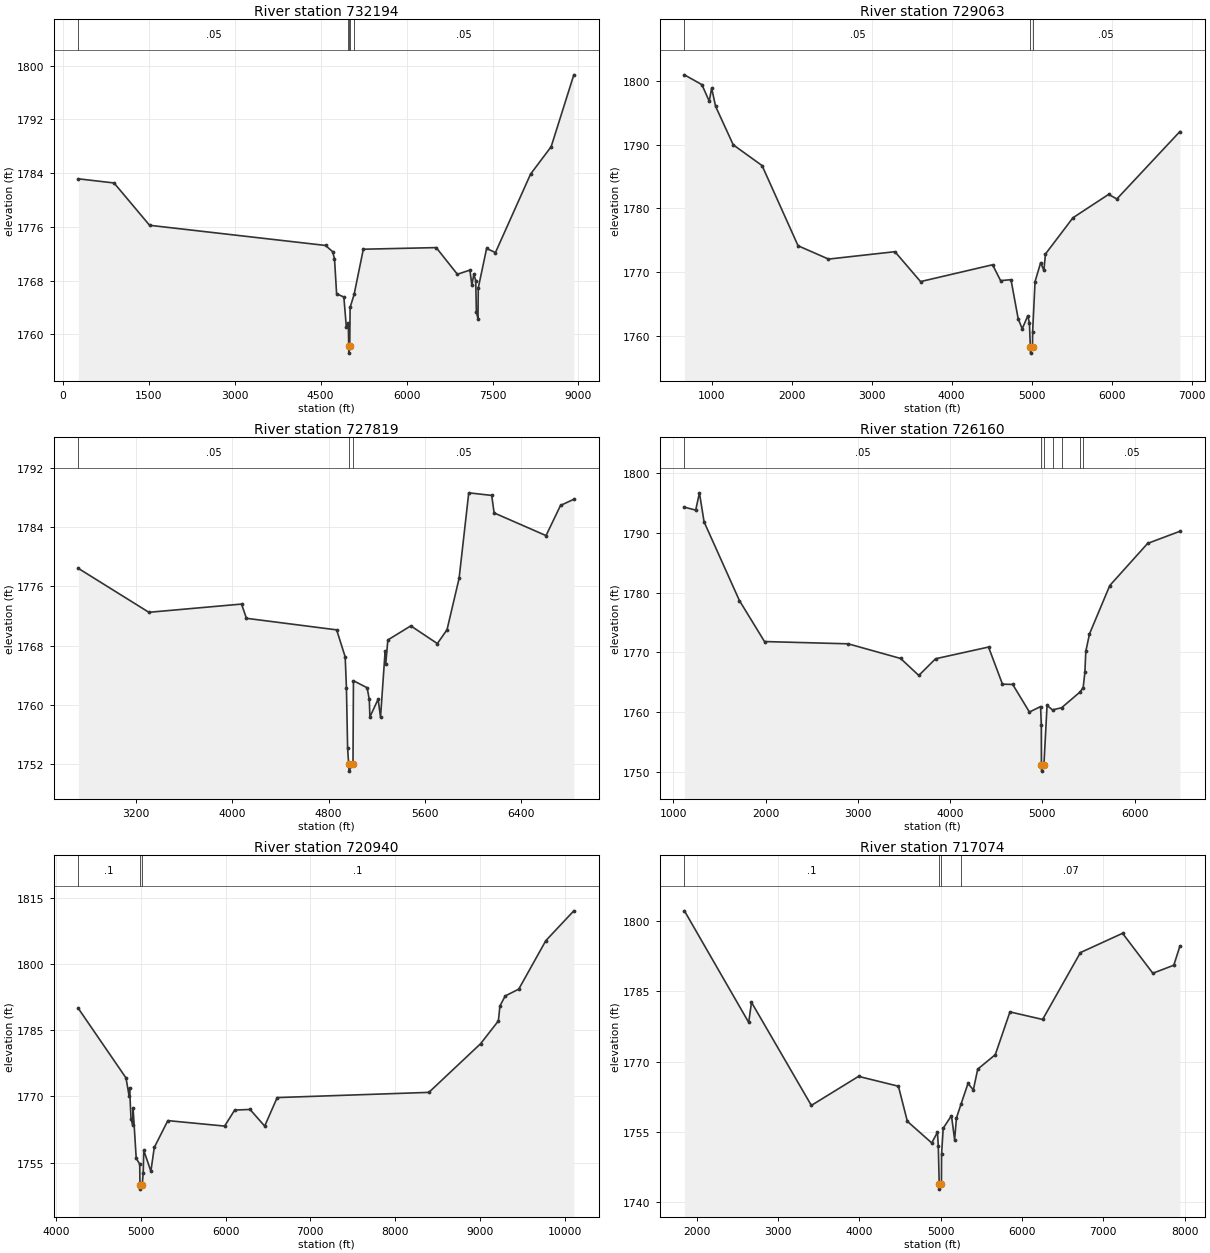
Type RM Length L Ch R = 1,732194,3131,3131,3131
BEGIN DESCRIPTION:
Clear Fork Brazos Rv 168.0
END DESCRIPTION:
XS GIS Cut Line= 3
      1464244.05      6930801.39      1465094.74      6926218.07
      1466188.26      6922382.08
#Sta/Elev= 30
   269.0 1783.14   892.9 1782.52  1513.3 1776.22  4584.9 1773.22  4706.9 1772.31
  4741.4 1771.27  4778.1 1766.03  4904.9 1765.54  4948.0 1761.08  4982.7 1761.70
  4989.6 1758.19  4991.1 1757.19  5007.6 1758.19  5013.9 1763.99  5083.7 1765.92
  5244.7 1772.66  6517.4 1772.90  6886.9 1768.93  7105.5 1769.55  7139.4 1767.31
  7173.2 1768.90  7207.0 1768.00  7218.3 1763.29  7246.1 1762.34  7251.3 1766.90
  7397.0 1772.77  7551.1 1772.16  8164.8 1783.85  8523.9 1787.92  8919.4 1798.62
#Mann=5,-1,0
   269.0    0.05       0  4982.7    0.12       0  4989.6    0.07       0
  5007.6    0.12       0  5083.7    0.05       0
Bank Sta=4989.6,5007.6
Exp/Cntr=0.3,0.1

Type RM Length L Ch R = 1,729063,1244,1244,1244
BEGIN DESCRIPTION:
Clear Fork Brazos Rv 167.0
END DESCRIPTION:
XS GIS Cut Line= 3
      1466955.00      6928787.98      1467046.44      6924741.61
      1467189.11      6922601.57
#Sta/Elev= 30
   661.5 1800.94   879.7 1799.40   971.6 1796.81  1001.6 1798.85  1051.6 1795.98
  1271.6 1789.96  1631.7 1786.71  2081.8 1774.13  2461.9 1772.04  3292.2 1773.20
  3612.2 1768.51  4512.5 1771.15  4612.5 1768.66  4742.6 1768.81  4832.8 1762.66
  4882.9 1761.11  4953.1 1763.16  4973.1 1761.99  4984.4 1758.29  4986.7 1757.29
  5011.4 1758.29  5013.2 1760.67  5043.3 1768.51  5113.4 1771.48  5153.5 1770.26
  5173.5 1772.84  5516.7 1778.52  5962.7 1782.19  6065.5 1781.47  6853.7 1792.05
#Mann=3,-1,0
   661.5    0.05       0  4984.4    0.05       0  5011.4    0.05       0
Bank Sta=4984.4,5011.4
Exp/Cntr=0.3,0.1

Type RM Length L Ch R = 1,727819,1659,1659,1659
BEGIN DESCRIPTION:
Mapping XS c1ba433a
END DESCRIPTION:
XS GIS Cut Line= 3
      1467482.39      6927536.84      1467873.97      6924991.62
      1467776.07      6923457.91
#Sta/Elev= 30
  2722.6 1778.41  3308.3 1772.48  4077.2 1773.59  4117.7 1771.67  4866.4 1770.11
  4937.2 1766.47  4947.6 1762.33  4957.4 1754.16  4966.0 1752.05  4969.0 1751.05
  5002.0 1752.05  5005.8 1763.25  5119.3 1762.30  5137.3 1760.72  5142.4 1758.37
  5210.7 1760.75  5230.6 1758.31  5268.9 1767.29  5273.9 1765.56  5291.3 1768.75
  5481.8 1770.65  5702.2 1768.26  5782.4 1770.13  5882.6 1777.06  5962.7 1788.60
  6153.1 1788.25  6173.2 1785.89  6604.0 1782.83  6724.3 1786.90  6834.6 1787.73
#Mann=3,-1,0
  2722.6    0.05       0  4966.0    0.05       0  5002.0    0.05       0
Bank Sta=4966,5002
Exp/Cntr=0.3,0.1

Type RM Length L Ch R = 1,726160,5220,5220,5220
BEGIN DESCRIPTION:
Clear Fork Brazos Rv 166.0
END DESCRIPTION:
XS GIS Cut Line= 3
      1469673.74      6928479.40      1469205.00      6924638.00
      1469205.00      6923137.99
#Sta/Elev= 30
  1121.0 1794.28  1243.3 1793.79  1283.6 1796.68  1334.0 1791.83  1716.8 1778.67
  1988.8 1771.81  2895.5 1771.43  3464.1 1768.98  3661.1 1766.14  3842.4 1768.93
  4416.7 1770.89  4567.8 1764.68  4678.6 1764.64  4859.9 1760.02  4980.8 1760.94
  4988.4 1757.93  4989.8 1751.14  4992.0 1750.14  5016.8 1751.14  5050.9 1761.12
  5110.5 1760.38  5208.4 1760.74  5407.4 1763.36  5442.2 1764.10  5460.9 1766.66
  5470.9 1770.17  5510.9 1773.09  5730.9 1781.18  6140.9 1788.22  6490.9 1790.25
#Mann=7,-1,0
  1121.0    0.05       0  4989.8    0.05       0  5016.8    0.05       0
  5110.5    0.12       0  5208.4    0.05       0  5407.4    0.12       0
  5442.2    0.05       0
Bank Sta=4989.8,5016.8
Exp/Cntr=0.3,0.1

Type RM Length L Ch R = 1,720940,3866,3866,3866
BEGIN DESCRIPTION:
Clear Fork Brazos Rv 165.0
END DESCRIPTION:
XS GIS Cut Line= 3
      1470741.46      6928062.74      1470559.15      6927307.48
      1470705.00      6922238.02
#Sta/Elev= 30
  4261.1 1789.95  4824.0 1774.18  4860.7 1770.07  4865.9 1771.96  4883.2 1764.91
  4902.6 1763.46  4907.7 1767.29  4944.5 1755.97  4986.1 1754.64  4988.5 1749.98
  4990.7 1748.98  5015.5 1749.98  5027.2 1752.70  5033.4 1757.78  5117.6 1753.03
  5157.6 1758.42  5317.6 1764.51  5987.9 1763.27  6106.8 1766.90  6288.0 1767.04
  6460.8 1763.27  6608.2 1769.73  8398.9 1770.91  9009.2 1781.94  9219.3 1787.11
  9237.3 1790.48  9299.3 1792.76  9459.4 1794.31  9779.5 1805.31 10109.6 1812.06
#Mann=3,-1,0
  4261.1     0.1       0  4988.5    0.05       0  5015.5     0.1       0
Bank Sta=4988.5,5015.5
Exp/Cntr=0.3,0.1

Type RM Length L Ch R = 1,717074,3105,3105,3105
BEGIN DESCRIPTION:
Clear Fork Brazos Rv 164.0
END DESCRIPTION:
XS GIS Cut Line= 3
      1472455.00      6928637.97      1472512.20      6925496.21
      1471991.44      6922593.94
#Sta/Elev= 30
  1851.2 1802.14  2641.3 1778.36  2675.7 1782.64  3411.4 1760.67  3991.5 1766.86
  4481.6 1764.76  4591.6 1757.28  4891.7 1752.67  4961.7 1754.97  4971.7 1752.10
  4983.5 1743.83  4985.8 1742.83  5010.5 1743.83  5012.0 1750.21  5032.3 1755.81
  5133.9 1758.49  5172.6 1753.34  5194.9 1757.99  5250.6 1760.91  5337.1 1765.35
  5402.7 1763.98  5456.4 1768.40  5672.4 1771.48  5852.7 1780.60  6254.1 1778.99
  6718.8 1793.24  7237.0 1797.35  7609.2 1788.84  7866.9 1790.55  7942.1 1794.64
#Mann=4,-1,0
  1851.2     0.1       0  4983.5    0.05       0  5010.5    0.07       0
  5250.6    0.07       0
Bank Sta=4983.5,5010.5
Exp/Cntr=0.3,0.1

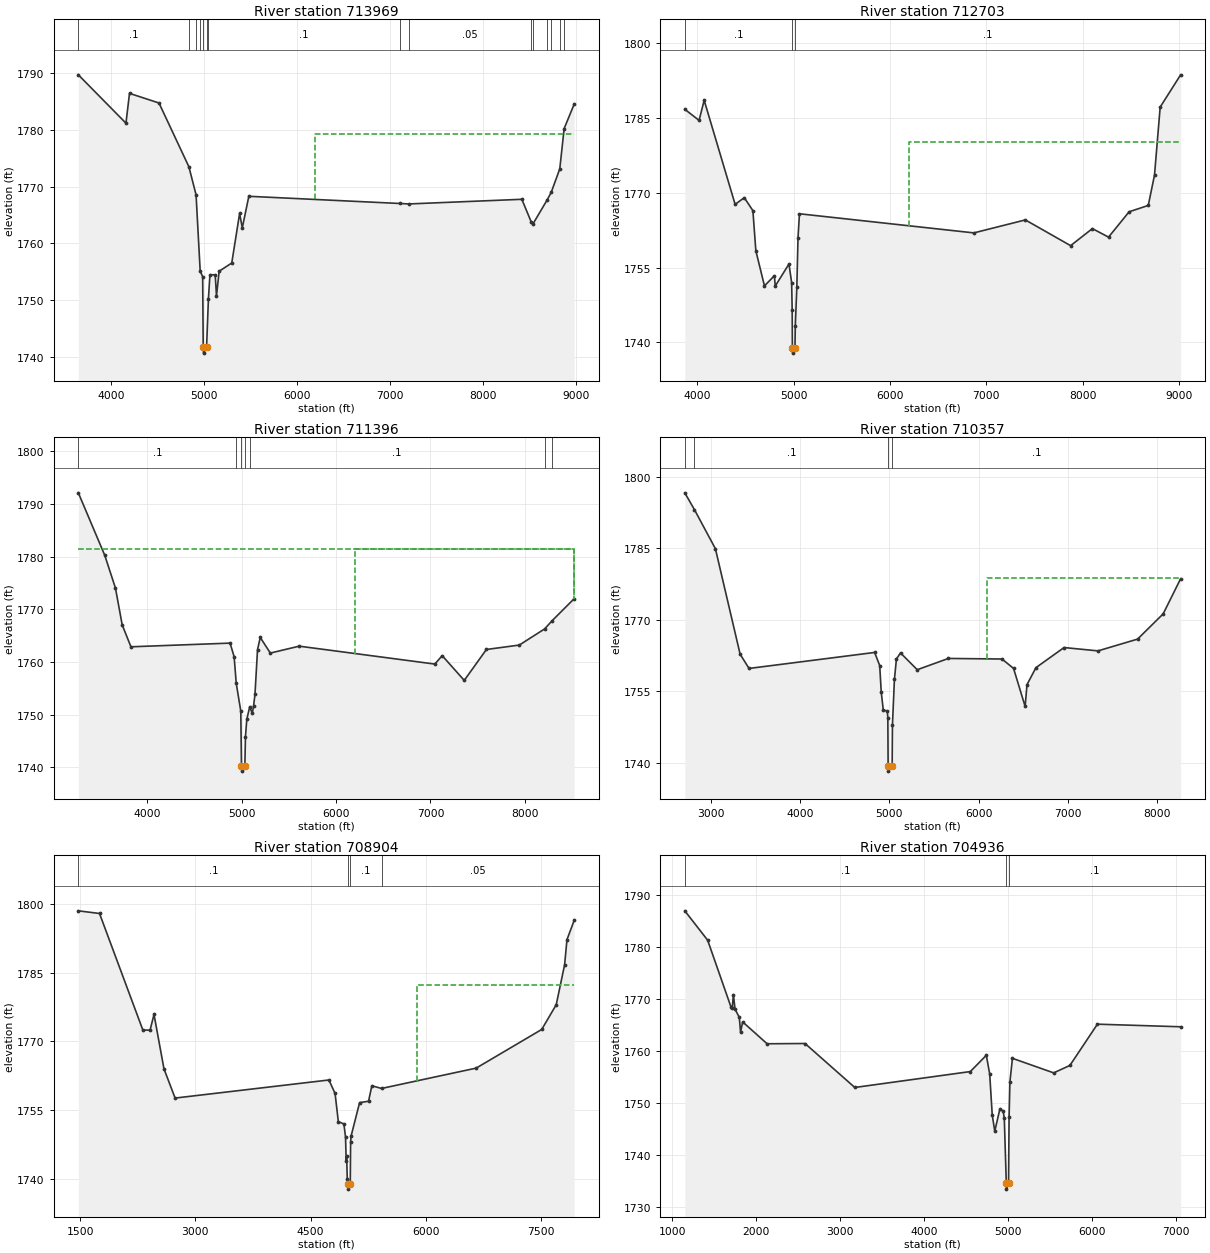
Type RM Length L Ch R = 1,713969,1266,1266,1266
BEGIN DESCRIPTION:
Mapping XS 6079fd2c
END DESCRIPTION:
XS GIS Cut Line= 4
      1472817.63      6928466.86      1473013.41      6927602.13
      1473894.46      6926525.30      1476129.71      6924436.89
#Sta/Elev= 30
  3647.7 1789.75  4160.4 1781.22  4198.5 1786.48  4515.9 1784.78  4837.7 1773.53
  4915.0 1768.58  4959.3 1755.12  4986.1 1754.14  4992.0 1741.65  4995.0 1740.65
  5028.0 1741.65  5048.0 1750.26  5064.4 1754.48  5121.1 1754.46  5134.7 1750.74
  5163.4 1755.10  5299.1 1756.55  5383.8 1765.30  5412.5 1762.75  5482.9 1768.32
  7109.1 1767.05  7205.5 1766.97  8421.6 1767.79  8524.2 1763.73  8539.1 1763.38
  8690.8 1767.59  8737.7 1769.01  8830.0 1773.17  8877.0 1780.27  8984.7 1784.57
#Mann=15,-1,0
  3647.7     0.1       0  4837.7    0.12       0  4915.0     0.1       0
  4959.3    0.12       0  4992.0    0.05       0  5028.0    0.12       0
  5048.0     0.1       0  7109.1    0.12       0  7205.5    0.05       0
  8524.2    0.12       0  8539.1    0.05       0  8690.8    0.12       0
  8737.7    0.05       0  8830.0    0.12       0  8877.0    0.05       0
#XS Ineff=2,0
       0                 6200.00    0.00 1779.35
Permanent Ineff=
       F       F
Bank Sta=4992,5028
Exp/Cntr=0.3,0.1

Type RM Length L Ch R = 1,712703,1307,1307,1307
BEGIN DESCRIPTION:
Clear Fork Brazos Rv 163.0
END DESCRIPTION:
XS GIS Cut Line= 3
      1473155.02      6928537.99      1474155.00      6928038.00
      1477654.97      6926038.02
#Sta/Elev= 30
  3869.7 1786.73  4017.8 1784.51  4070.9 1788.53  4392.4 1767.67  4487.4 1769.02
  4576.8 1766.42  4607.6 1758.37  4697.0 1751.34  4800.4 1753.38  4808.8 1751.30
  4951.4 1755.72  4979.3 1752.01  4984.9 1746.41  4986.9 1738.96  4989.2 1737.86
  5013.9 1738.96  5017.2 1743.26  5033.1 1751.08  5045.3 1760.93  5060.4 1765.79
  6871.5 1761.96  7406.4 1764.56  7876.4 1759.40  8102.5 1762.82  8270.2 1761.11
  8484.0 1766.19  8682.7 1767.46  8747.5 1773.53  8806.5 1787.18  9018.8 1793.64
#Mann=3,-1,0
  3869.7     0.1       0  4986.9    0.05       0  5013.9     0.1       0
#XS Ineff=2,0
       0                 6200.00    0.00 1780.15
Permanent Ineff=
       F       F
Bank Sta=4986.9,5013.9
Exp/Cntr=0.3,0.1

Type RM Length L Ch R = 1,711396,1039,1039,1039
BEGIN DESCRIPTION:
Mapping XS d30e98d7
END DESCRIPTION:
XS GIS Cut Line= 3
      1473829.21      6930196.33      1474906.04      6928907.39
      1477679.73      6926655.80
#Sta/Elev= 30
  3270.0 1792.10  3550.0 1780.23  3663.2 1774.01  3734.8 1767.01  3827.2 1762.86
  4877.4 1763.56  4920.4 1760.97  4942.5 1755.96  4990.8 1750.64  4998.0 1740.25
  5001.0 1739.25  5034.0 1740.25  5040.3 1745.78  5054.7 1749.11  5085.7 1751.49
  5112.2 1750.20  5126.6 1751.67  5141.0 1753.81  5168.2 1762.33  5197.0 1764.63
  5304.0 1761.67  5609.3 1762.98  7046.1 1759.58  7124.4 1761.18  7357.8 1756.48
  7592.7 1762.35  7941.2 1763.19  8208.6 1766.25  8290.8 1767.85  8522.1 1772.00
#Mann=7,-1,0
  3270.0     0.1       0  4942.5    0.12       0  4998.0    0.05       0
  5034.0    0.12       0  5085.7     0.1       0  8208.6    0.12       0
  8290.8    0.05       0
#XS Ineff=2,0
    0.00 3153.10 1781.49 6200.00    0.00 1781.49
Permanent Ineff=
       F       F
Bank Sta=4998,5034
Exp/Cntr=0.3,0.1

Type RM Length L Ch R = 1,710357,1453,1453,1453
BEGIN DESCRIPTION:
Mapping XS ed52b66a
END DESCRIPTION:
XS GIS Cut Line= 3
      1474857.07      6931387.42      1476064.45      6928842.13
      1478267.04      6927226.90
#Sta/Elev= 30
  2712.1 1796.66  2820.3 1793.12  3054.6 1784.92  3331.3 1762.76  3430.9 1759.77
  4836.5 1763.13  4893.1 1760.38  4910.3 1754.82  4933.1 1751.05  4978.5 1750.80
  4984.1 1749.44  4987.5 1739.20  4991.3 1738.20  5032.5 1739.20  5035.7 1747.91
  5057.9 1757.47  5080.5 1761.78  5126.0 1763.03  5313.4 1759.50  5661.6 1761.87
  6261.6 1761.75  6391.0 1759.78  6520.6 1751.79  6541.5 1756.37  6641.8 1759.94
  6956.0 1764.16  7335.7 1763.46  7778.7 1765.93  8065.1 1771.23  8260.6 1778.61
#Mann=4,-1,0
  2712.1    0.12       0  2820.3     0.1       0  4987.5    0.05       0
  5032.5     0.1       0
#XS Ineff=2,0
       0                 6098.60    0.00 1778.80
Permanent Ineff=
       F       F
Bank Sta=4987.5,5032.5
Exp/Cntr=0.3,0.1

Type RM Length L Ch R = 1,708904,3968,3968,3968
BEGIN DESCRIPTION:
Clear Fork Brazos Rv 162.0
END DESCRIPTION:
XS GIS Cut Line= 3
      1475220.63      6932645.99      1477155.00      6929688.00
      1478655.00      6927188.00
#Sta/Elev= 30
  1477.5 1798.48  1753.1 1797.90  2317.1 1772.43  2410.6 1772.42  2461.9 1775.84
  2591.6 1763.96  2736.4 1757.58  4737.0 1761.53  4817.3 1758.59  4859.5 1752.44
  4931.9 1751.93  4953.0 1749.10  4962.1 1743.89  4968.1 1744.85  4976.0 1739.86
  4987.8 1738.79  4990.0 1737.69  5014.8 1738.79  5019.6 1748.08  5025.4 1749.27
  5136.2 1756.58  5252.8 1756.89  5295.6 1760.27  5421.5 1759.68  6652.3 1764.12
  7505.5 1772.57  7694.1 1777.97  7802.9 1786.68  7834.0 1792.19  7927.3 1796.38
#Mann=4,-1,0
  1477.5     0.1       0  4987.8    0.05       0  5014.8     0.1       0
  5421.5    0.05       0
#XS Ineff=2,0
       0                 5881.20    0.00 1782.29
Permanent Ineff=
       F       F
Bank Sta=4987.8,5014.8
Exp/Cntr=0.3,0.1

Type RM Length L Ch R = 1,704936,3449,3449,3449
BEGIN DESCRIPTION:
Clear Fork Brazos Rv 161.0
END DESCRIPTION:
XS GIS Cut Line= 3
      1478762.28      6935224.14      1479155.00      6931388.00
      1479309.16      6929338.68
#Sta/Elev= 30
  1149.0 1786.94  1421.4 1781.29  1698.0 1768.51  1714.4 1768.17  1728.2 1770.81
  1748.3 1768.00  1798.5 1766.46  1813.8 1763.58  1838.7 1765.57  2130.2 1761.36
  2582.6 1761.41  3175.7 1752.95  4552.8 1756.01  4743.8 1759.14  4784.0 1755.55
  4814.2 1747.68  4844.4 1744.54  4904.7 1748.76  4944.9 1748.42  4958.0 1747.03
  4982.0 1734.59  4984.3 1733.39  5009.0 1734.59  5015.2 1747.31  5025.2 1754.06
  5055.3 1758.56  5546.7 1755.76  5740.3 1757.19  6068.2 1765.13  7060.3 1764.63
#Mann=3,-1,0
  1149.0     0.1       0  4982.0    0.05       0  5009.0     0.1       0
Bank Sta=4982,5009
Exp/Cntr=0.3,0.1

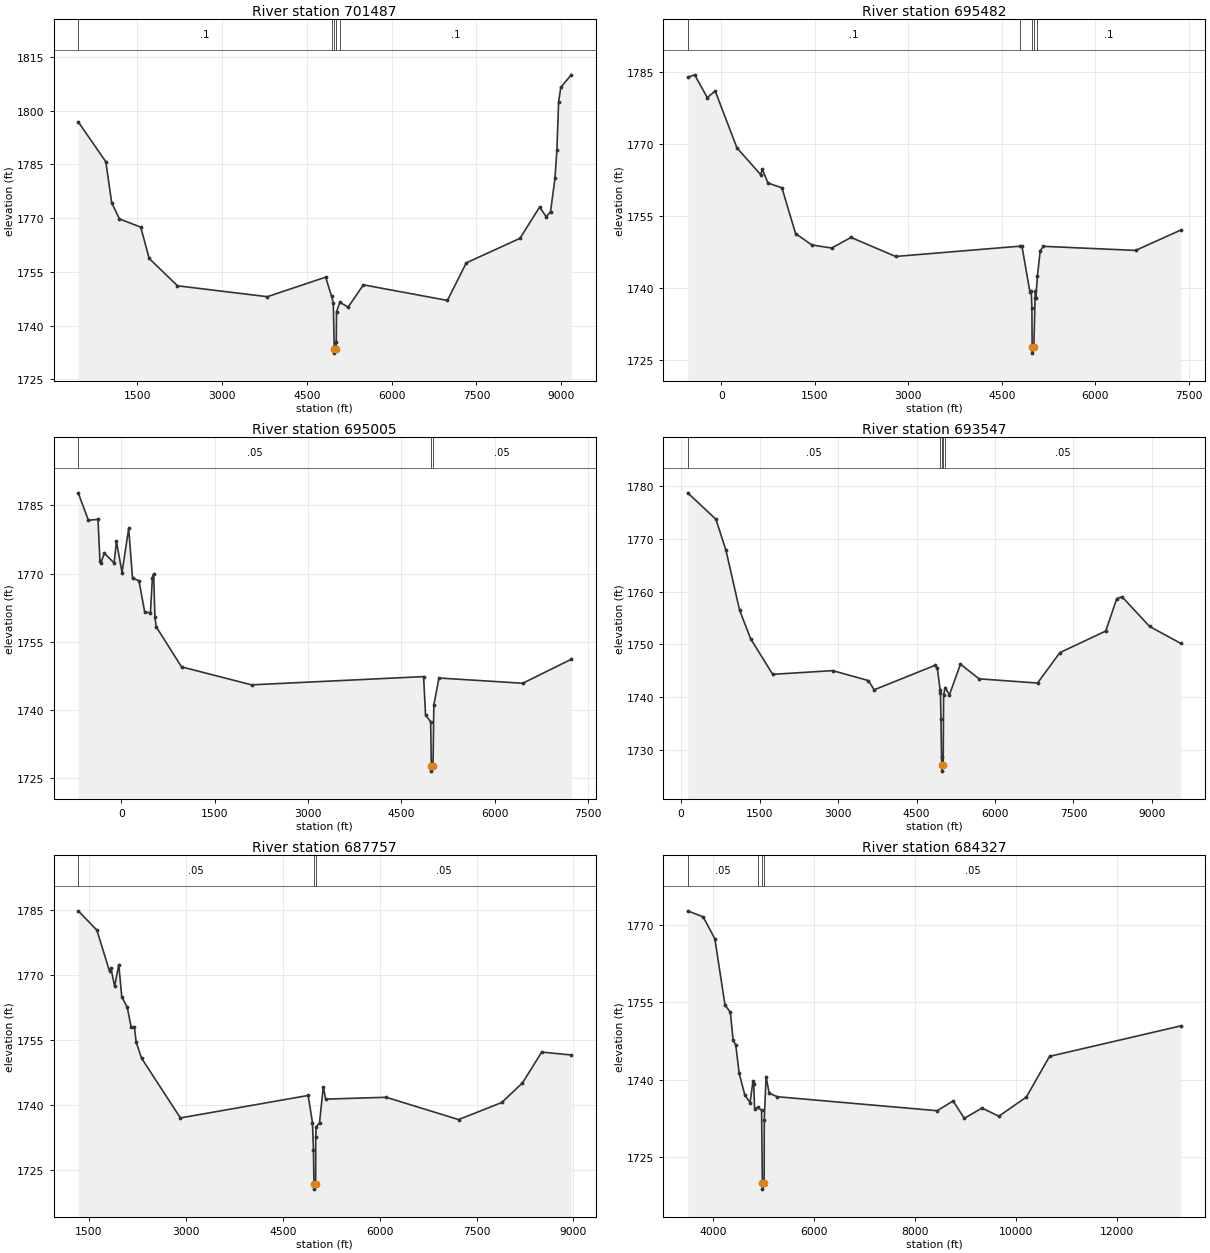
Type RM Length L Ch R = 1,701487,6005,6005,6005
BEGIN DESCRIPTION:
Clear Fork Brazos Rv 160.0
END DESCRIPTION:
XS GIS Cut Line= 3
      1481184.15      6937125.22      1482155.00      6932688.00
      1481355.00      6928588.01
#Sta/Elev= 30
   457.9 1796.88   946.4 1785.73  1050.3 1774.27  1187.0 1769.78  1563.5 1767.48
  1714.1 1758.73  2213.5 1751.11  3802.2 1748.07  4833.8 1753.52  4938.4 1748.16
  4969.4 1746.30  4985.8 1733.52  4988.0 1732.32  5012.8 1733.52  5020.5 1735.37
  5025.9 1743.87  5083.7 1746.49  5232.2 1745.16  5500.3 1751.38  6986.9 1747.03
  7320.9 1757.52  8270.6 1764.36  8617.0 1773.09  8733.9 1770.38  8810.6 1771.84
  8888.6 1781.08  8922.7 1789.08  8953.3 1802.38  8991.8 1806.52  9177.4 1809.99
#Mann=5,-1,0
   457.9     0.1       0  4938.4     0.1       0  4985.8    0.05       0
  5012.8     0.1       0  5083.7     0.1       0
Bank Sta=4985.8,5012.8
Exp/Cntr=0.3,0.1

Type RM Length L Ch R = 1,695482,477,477,477
BEGIN DESCRIPTION:
Mapping XS f4c9daf9
END DESCRIPTION:
XS GIS Cut Line= 2
      1483088.56      6937458.10      1484876.39      6929751.35
#Sta/Elev= 30
  -540.4 1783.91  -427.4 1784.44  -225.7 1779.68   -98.9 1781.08   250.1 1769.22
   630.0 1763.65   658.2 1764.72   748.6 1761.88   972.2 1760.89  1190.6 1751.35
  1451.2 1748.98  1770.8 1748.33  2079.7 1750.55  2796.0 1746.58  4786.7 1748.72
  4821.9 1748.81  4949.9 1739.25  4972.3 1739.37  4982.6 1735.87  4986.5 1727.63
  4988.8 1726.43  5013.5 1727.63  5033.9 1737.93  5040.3 1739.31  5045.5 1737.96
  5071.0 1742.47  5116.0 1747.78  5167.3 1748.69  6645.6 1747.84  7371.0 1752.08
#Mann=5,-1,0
  -540.4     0.1       0  4786.7     0.1       0  4986.5    0.05       0
  5013.5     0.1       0  5071.0     0.1       0
Bank Sta=4986.5,5013.5
Exp/Cntr=0.3,0.1

Type RM Length L Ch R = 1,695005,1458,1458,1458
BEGIN DESCRIPTION:
Mapping XS 9c229a51
END DESCRIPTION:
XS GIS Cut Line= 2
      1483487.87      6937527.55      1485310.80      6929819.17
#Sta/Elev= 30
  -692.3 1787.74  -528.3 1781.71  -374.0 1781.91  -343.4 1772.80  -331.7 1772.28
  -271.5 1774.47  -115.2 1772.32   -78.0 1777.09    11.7 1770.21   119.0 1779.95
   180.7 1768.94   283.4 1768.45   375.9 1761.57   468.4 1761.39   499.2 1769.06
   519.8 1769.94   540.3 1760.47   560.9 1758.31   967.5 1749.50  2092.0 1745.55
  4856.2 1747.36  4887.0 1739.03  4970.0 1737.38  4980.5 1727.79  4982.8 1726.59
  5007.5 1727.79  5020.6 1741.10  5102.8 1747.05  6448.9 1745.90  7228.7 1751.17
#Mann=3,-1,0
  -692.3    0.05       0  4980.5   0.035       0  5007.5    0.05       0
Bank Sta=4980.5,5007.5
Exp/Cntr=0.3,0.1

Type RM Length L Ch R = 1,693547,5790,5790,5790
BEGIN DESCRIPTION:
Clear Fork Brazos Rv 159.0
END DESCRIPTION:
XS GIS Cut Line= 3
      1486704.98      6936734.55      1486205.00      6931888.00
      1485715.58      6927361.25
#Sta/Elev= 30
   125.6 1778.71   665.7 1773.70   858.7 1767.78  1117.4 1756.50  1328.5 1751.06
  1750.7 1744.30  2896.8 1745.00  3580.1 1743.12  3691.0 1741.37  4851.9 1746.00
  4897.3 1745.50  4951.2 1741.34  4957.7 1740.79  4967.7 1735.92  4977.8 1728.72
  4982.8 1727.15  4985.1 1725.95  5009.8 1727.15  5018.0 1740.42  5049.9 1741.78
  5128.6 1740.40  5339.8 1746.23  5696.3 1743.45  6812.7 1742.65  7240.9 1748.42
  8117.7 1752.51  8327.2 1758.65  8427.7 1759.02  8953.8 1753.39  9551.0 1750.17
#Mann=5,-1,0
   125.6    0.05       0  4951.2     0.1       0  4982.8    0.07       0
  5009.8     0.1       0  5049.9    0.05       0
Bank Sta=4982.8,5009.8
Exp/Cntr=0.3,0.1

Type RM Length L Ch R = 1,687757,3430,3430,3430
BEGIN DESCRIPTION:
Mapping XS f4ade710
END DESCRIPTION:
XS GIS Cut Line= 2
      1491314.37      6933974.17      1487329.98      6927463.73
#Sta/Elev= 30
  1333.8 1784.85  1622.4 1780.41  1818.5 1770.94  1839.8 1771.68  1897.8 1767.44
  1962.4 1772.44  2008.1 1765.03  2093.3 1762.60  2151.3 1758.17  2203.5 1757.95
  2232.1 1754.57  2313.7 1750.89  2915.5 1737.09  4893.4 1742.27  4960.4 1735.98
  4975.5 1729.72  4982.8 1721.87  4985.0 1720.67  5009.8 1721.87  5010.7 1732.73
  5018.4 1735.08  5069.3 1735.95  5127.9 1744.30  5163.1 1741.43  6101.0 1741.85
  7222.0 1736.71  7891.4 1740.65  8211.3 1745.17  8508.6 1752.27  8966.7 1751.61
#Mann=3,-1,0
  1333.8    0.05       0  4982.8    0.05       0  5009.8    0.05       0
Bank Sta=4982.8,5009.8
Exp/Cntr=0.3,0.1

Type RM Length L Ch R = 1,684327,5119,5119,5119
BEGIN DESCRIPTION:
Mapping XS 35d44dbe
END DESCRIPTION:
XS GIS Cut Line= 3
      1493319.55      6932229.32      1492850.82      6931526.23
      1488789.17      6923585.18
#Sta/Elev= 30
  3496.2 1772.79  3803.1 1771.62  4034.4 1767.37  4235.7 1754.50  4341.2 1753.10
  4395.4 1747.78  4449.4 1746.68  4516.0 1741.28  4627.1 1737.05  4732.4 1735.56
  4788.5 1739.67  4804.8 1739.11  4821.4 1734.35  4884.0 1734.61  4960.3 1734.07
  4975.0 1719.96  4978.0 1718.76  5011.0 1719.96  5013.2 1732.26  5049.1 1740.58
  5110.1 1737.38  5271.5 1736.70  8439.0 1733.98  8752.4 1735.88  8974.6 1732.50
  9324.3 1734.50  9657.5 1732.92 10201.6 1736.61 10662.4 1744.53 13260.7 1750.45
#Mann=4,-1,0
  3496.2    0.05       0  4884.0     0.1       0  4975.0    0.07       0
  5011.0    0.05       0
Bank Sta=4975,5011
Exp/Cntr=0.3,0.1

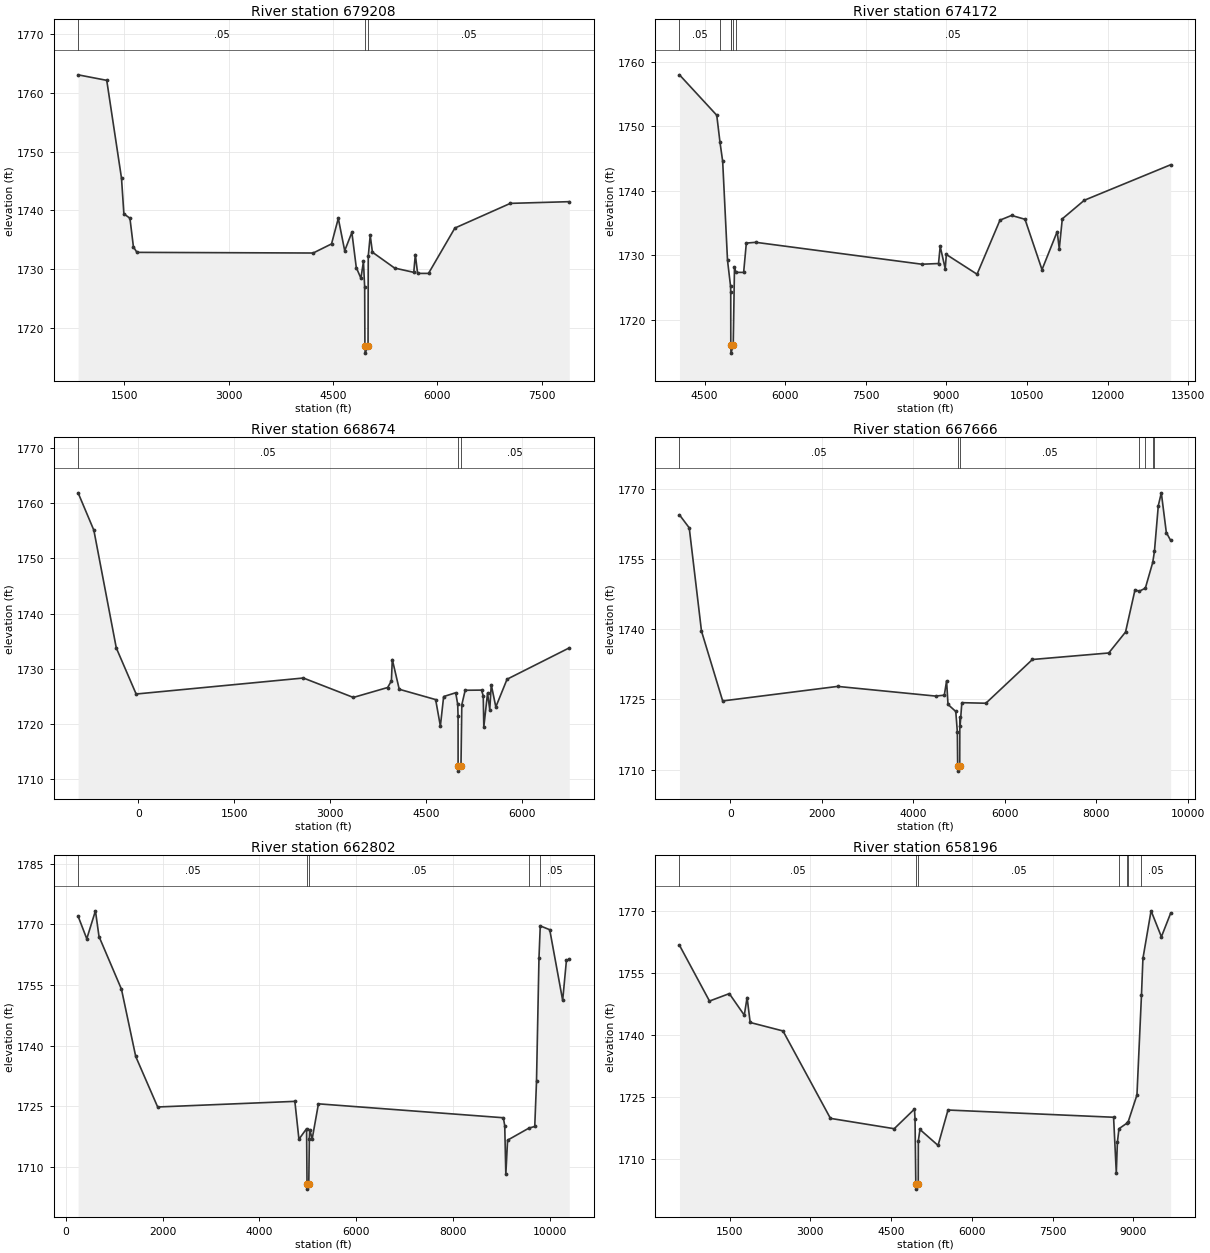
Type RM Length L Ch R = 1,679208,5036,5036,5036
BEGIN DESCRIPTION:
Clear Fork Brazos Rv 156.0
END DESCRIPTION:
XS GIS Cut Line= 3
      1494998.37      6931635.90      1494711.91      6929526.51
      1492654.61      6925047.33
#Sta/Elev= 30
   838.3 1763.07  1249.9 1762.13  1461.9 1745.48  1496.1 1739.41  1583.0 1738.66
  1633.4 1733.77  1683.9 1732.85  4215.9 1732.74  4479.8 1734.29  4577.2 1738.64
  4669.1 1733.13  4772.1 1736.25  4835.5 1730.27  4902.2 1728.44  4938.5 1731.31
  4956.0 1726.91  4959.5 1716.90  4963.2 1715.70  5004.5 1716.90  5007.4 1732.17
  5035.9 1735.76  5067.2 1732.88  5386.2 1730.18  5661.5 1729.45  5684.0 1732.48
  5716.5 1729.27  5873.4 1729.27  6252.1 1736.99  7049.1 1741.19  7896.1 1741.48
#Mann=3,-1,0
   838.3    0.05       0  4959.5    0.03       0  5004.5    0.05       0
Bank Sta=4959.5,5004.5
Exp/Cntr=0.3,0.1

Type RM Length L Ch R = 1,674172,5498,5498,5498
BEGIN DESCRIPTION:
Mapping XS 67d2fc04
END DESCRIPTION:
XS GIS Cut Line= 3
      1496430.66      6931401.49      1496378.57      6929943.17
      1494217.10      6922573.35
#Sta/Elev= 30
  4033.5 1757.99  4727.4 1751.72  4788.1 1747.50  4837.5 1744.58  4927.6 1729.21
  4984.1 1725.21  4987.6 1724.28  4988.8 1716.02  4992.6 1714.82  5033.8 1716.02
  5057.6 1728.20  5082.2 1727.35  5227.8 1727.34  5277.8 1731.89  5452.8 1732.01
  8544.9 1728.61  8853.8 1728.72  8885.0 1731.37  8978.8 1727.91  8999.7 1730.12
  9570.8 1727.06  9997.6 1735.45 10213.6 1736.18 10463.0 1735.58 10779.3 1727.77
 11062.1 1733.67 11100.7 1731.00 11156.9 1735.65 11566.1 1738.53 13173.0 1744.04
#Mann=6,-1,0
  4033.5    0.05       0  4788.1     0.1       0  4984.1    0.12       0
  4988.8    0.07       0  5033.8    0.12       0  5082.2    0.05       0
Bank Sta=4988.8,5033.8
Exp/Cntr=0.3,0.1

Type RM Length L Ch R = 1,668674,1008,1008,1008
BEGIN DESCRIPTION:
Mapping XS d4f81cd9
END DESCRIPTION:
XS GIS Cut Line= 3
      1498369.90      6931254.02      1498612.95      6926913.78
      1496911.56      6924049.19
#Sta/Elev= 30
  -943.2 1761.89  -696.8 1755.11  -346.2 1733.79   -35.8 1725.44  2578.3 1728.34
  3359.6 1724.82  3896.2 1726.62  3954.7 1727.81  3968.8 1731.69  4077.4 1726.30
  4646.3 1724.43  4720.3 1719.63  4771.4 1724.98  4960.0 1725.67  4991.2 1723.59
  4997.0 1721.38  4997.5 1712.47  5001.3 1711.47  5042.5 1712.47  5055.4 1723.49
  5108.1 1726.12  5363.3 1726.15  5390.5 1725.10  5399.4 1719.46  5457.6 1725.61
  5492.5 1722.60  5515.7 1727.13  5587.3 1723.10  5762.7 1728.12  6735.6 1733.80
#Mann=3,-1,0
  -943.2    0.05       0  4997.5   0.035       0  5042.5    0.05       0
Bank Sta=4997.5,5042.5
Exp/Cntr=0.3,0.1

Type RM Length L Ch R = 1,667666,4864,4864,4864
BEGIN DESCRIPTION:
Mapping XS 38bf1977
END DESCRIPTION:
XS GIS Cut Line= 3
      1498689.68      6931291.53      1499019.54      6926031.06
      1496432.74      6921204.68
#Sta/Elev= 30
 -1116.1 1764.38  -902.2 1761.61  -634.1 1739.58  -170.7 1724.69  2344.2 1727.79
  4487.0 1725.73  4678.7 1725.92  4728.2 1728.97  4759.5 1723.94  4929.7 1722.44
  4963.8 1718.06  4970.7 1710.92  4974.5 1709.72  5015.7 1710.92  5018.2 1721.20
  5023.9 1719.37  5062.1 1724.32  5587.6 1724.20  6606.2 1733.53  8276.3 1734.92
  8643.4 1739.38  8851.4 1748.41  8941.8 1748.08  9076.8 1748.74  9238.9 1754.24
  9275.9 1756.58  9360.7 1766.35  9426.5 1769.08  9536.1 1760.61  9630.6 1758.93
#Mann=7,-1,0
 -1116.1    0.05       0  4970.7    0.05       0  5015.7    0.05       0
  8941.8    0.12       0  9076.8    0.05       0  9238.9    0.12       0
  9275.9    0.05       0
Bank Sta=4970.7,5015.7
Exp/Cntr=0.3,0.1

Type RM Length L Ch R = 1,662802,4606,4606,4606
BEGIN DESCRIPTION:
Clear Fork Brazos Rv 154.0
END DESCRIPTION:
XS GIS Cut Line= 3
      1498855.00      6931988.00      1500355.00      6927488.00
      1503354.98      6922988.03
#Sta/Elev= 30
   255.6 1772.00   434.8 1766.41   614.0 1773.32   687.8 1766.97  1151.6 1753.96
  1446.7 1737.32  1900.0 1724.84  4735.5 1726.23  4819.8 1716.87  4977.9 1719.49
  4987.0 1705.74  4990.0 1704.54  5023.0 1705.74  5035.1 1717.01  5042.6 1719.24
  5093.7 1716.96  5222.9 1725.62  9044.7 1722.18  9073.3 1720.20  9095.8 1708.19
  9131.9 1716.64  9576.4 1719.64  9693.7 1720.02  9729.8 1731.14  9780.9 1761.65
  9807.5 1769.60 10003.2 1768.65 10270.6 1751.19 10348.8 1761.14 10407.3 1761.32
#Mann=5,-1,0
   255.6    0.05       0  4987.0    0.05       0  5023.0    0.05       0
  9576.4    0.12       0  9807.5    0.05       0
Bank Sta=4987,5023
Exp/Cntr=0.3,0.1

Type RM Length L Ch R = 1,658196,3659,3659,3659
BEGIN DESCRIPTION:
Clear Fork Brazos Rv 153.0
END DESCRIPTION:
XS GIS Cut Line= 3
      1501855.00      6932437.97      1502756.61      6927703.59
      1503355.00      6923438.03
#Sta/Elev= 30
   567.9 1761.63  1125.9 1748.13  1494.2 1749.93  1772.4 1744.72  1824.6 1748.99
  1881.8 1742.95  2491.8 1740.90  3373.3 1719.76  4558.3 1717.26  4935.0 1722.01
  4945.2 1719.52  4959.6 1703.85  4963.4 1702.65  5004.6 1703.85  5006.2 1714.32
  5036.8 1717.07  5372.7 1713.22  5557.7 1721.78  8634.4 1720.03  8684.9 1706.61
  8705.1 1713.97  8734.6 1717.26  8887.8 1718.65  8907.1 1718.99  9068.7 1725.42
  9152.9 1749.64  9179.7 1758.43  9331.2 1769.95  9523.1 1763.67  9694.7 1769.38
#Mann=7,-1,0
   567.9    0.05       0  4959.6    0.05       0  5004.6    0.05       0
  8734.6    0.12       0  8887.8     0.1       0  8907.1    0.12       0
  9152.9    0.05       0
Bank Sta=4959.6,5004.6
Exp/Cntr=0.3,0.1

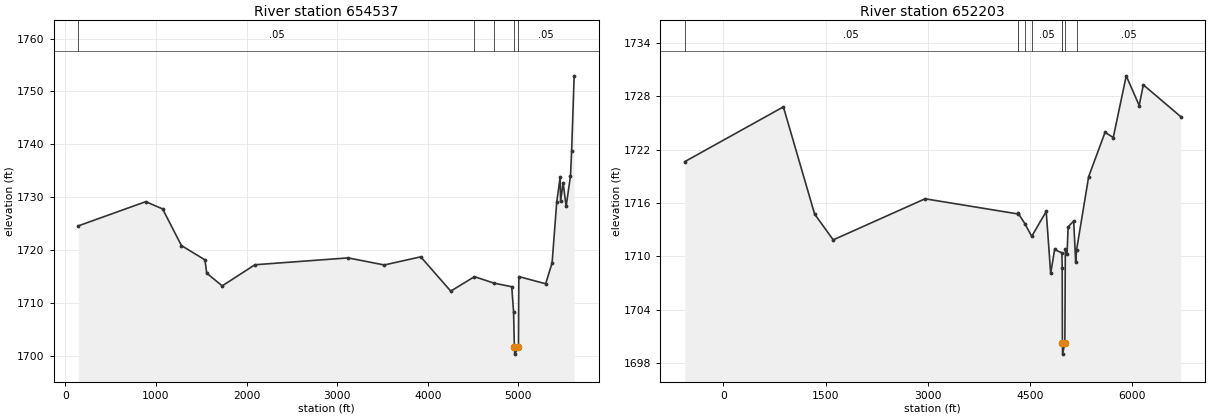
Type RM Length L Ch R = 1,654537,2334,2334,2334
BEGIN DESCRIPTION:
Clear Fork Brazos Rv 152.0
END DESCRIPTION:
XS GIS Cut Line= 3
      1504178.94      6930328.36      1504655.00      6925488.00
      1504755.00      6924887.99
#Sta/Elev= 30
   143.9 1724.61   887.8 1729.18  1074.0 1727.81  1281.7 1720.89  1541.0 1718.19
  1561.1 1715.67  1731.9 1713.27  2092.2 1717.26  3120.6 1718.56  3520.5 1717.22
  3922.4 1718.76  4254.0 1712.28  4515.7 1715.01  4731.8 1713.79  4927.2 1713.11
  4947.3 1708.36  4956.2 1701.68  4960.0 1700.38  5001.2 1701.68  5005.1 1715.03
  5301.6 1713.67  5372.6 1717.63  5423.3 1729.06  5461.3 1733.81  5466.4 1729.26
  5494.2 1732.77  5527.2 1728.28  5575.3 1734.03  5588.0 1738.76  5615.9 1752.95
#Mann=5,-1,0
   143.9    0.05       0  4515.7    0.12       0  4731.8    0.05       0
  4956.2    0.04       0  5001.2    0.05       0
Bank Sta=4956.2,5001.2
Exp/Cntr=0.3,0.1

Type RM Length L Ch R = 1,652203,3380,3380,3380
BEGIN DESCRIPTION:
Clear Fork Brazos Rv 151.0
END DESCRIPTION:
XS GIS Cut Line= 3
      1505042.50      6930902.59      1506686.26      6925514.35
      1506809.04      6923871.52
#Sta/Elev= 30
  -566.9 1720.64   880.7 1726.80  1339.6 1714.74  1612.5 1711.84  2961.2 1716.46
  4322.1 1714.76  4324.3 1714.88  4425.8 1713.68  4527.2 1712.23  4740.2 1715.04
  4805.8 1708.07  4864.0 1710.76  4970.9 1710.37  4975.1 1708.71  4977.8 1700.29
  4980.8 1698.99  5013.8 1700.29  5020.9 1710.81  5046.0 1710.25  5062.0 1713.30
  5143.1 1713.96  5173.1 1709.34  5186.2 1710.73  5363.7 1718.96  5604.3 1723.94
  5724.7 1723.35  5915.2 1730.29  6105.7 1726.95  6165.9 1729.28  6713.9 1725.71
#Mann=9,-1,0
  -566.9    0.05       0  4322.1     0.1       0  4324.3    0.05       0
  4425.8     0.1       0  4527.2    0.05       0  4970.9     0.1       0
  4977.8    0.07       0  5013.8     0.1       0  5186.2    0.05       0
Bank Sta=4977.8,5013.8
Exp/Cntr=0.3,0.1