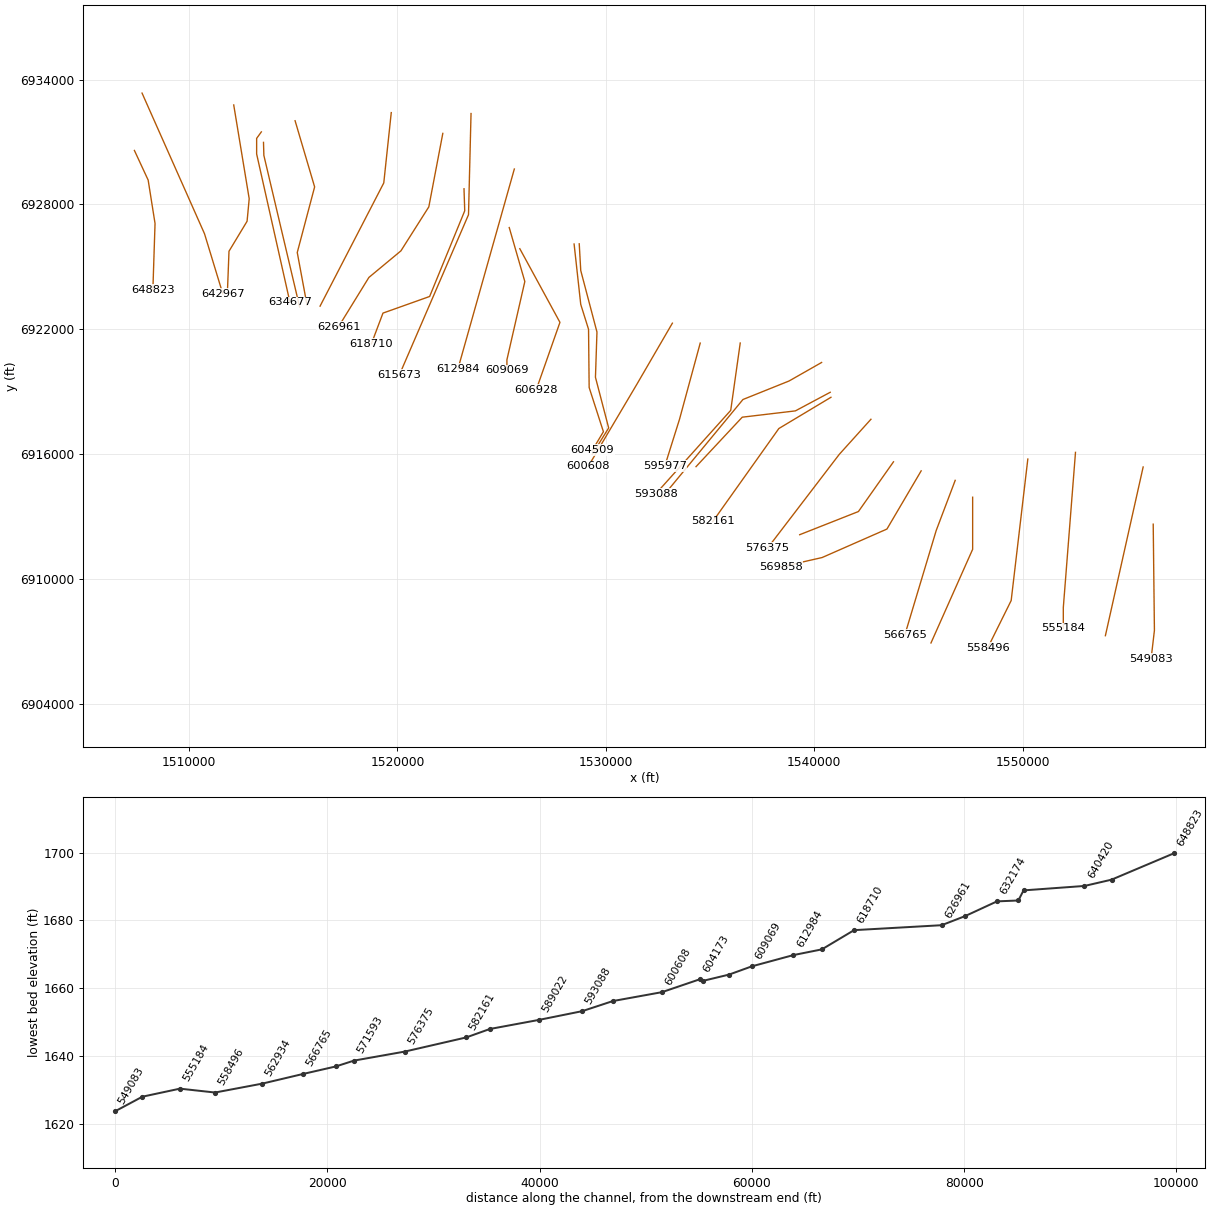
HEC-RAS study Clear Fork Brazos Rv.prj: Clear Fork Brazos Rv Base Level Engineering

--- Clear Fork Brazos Rv.g01 (geometry) --- (continued)

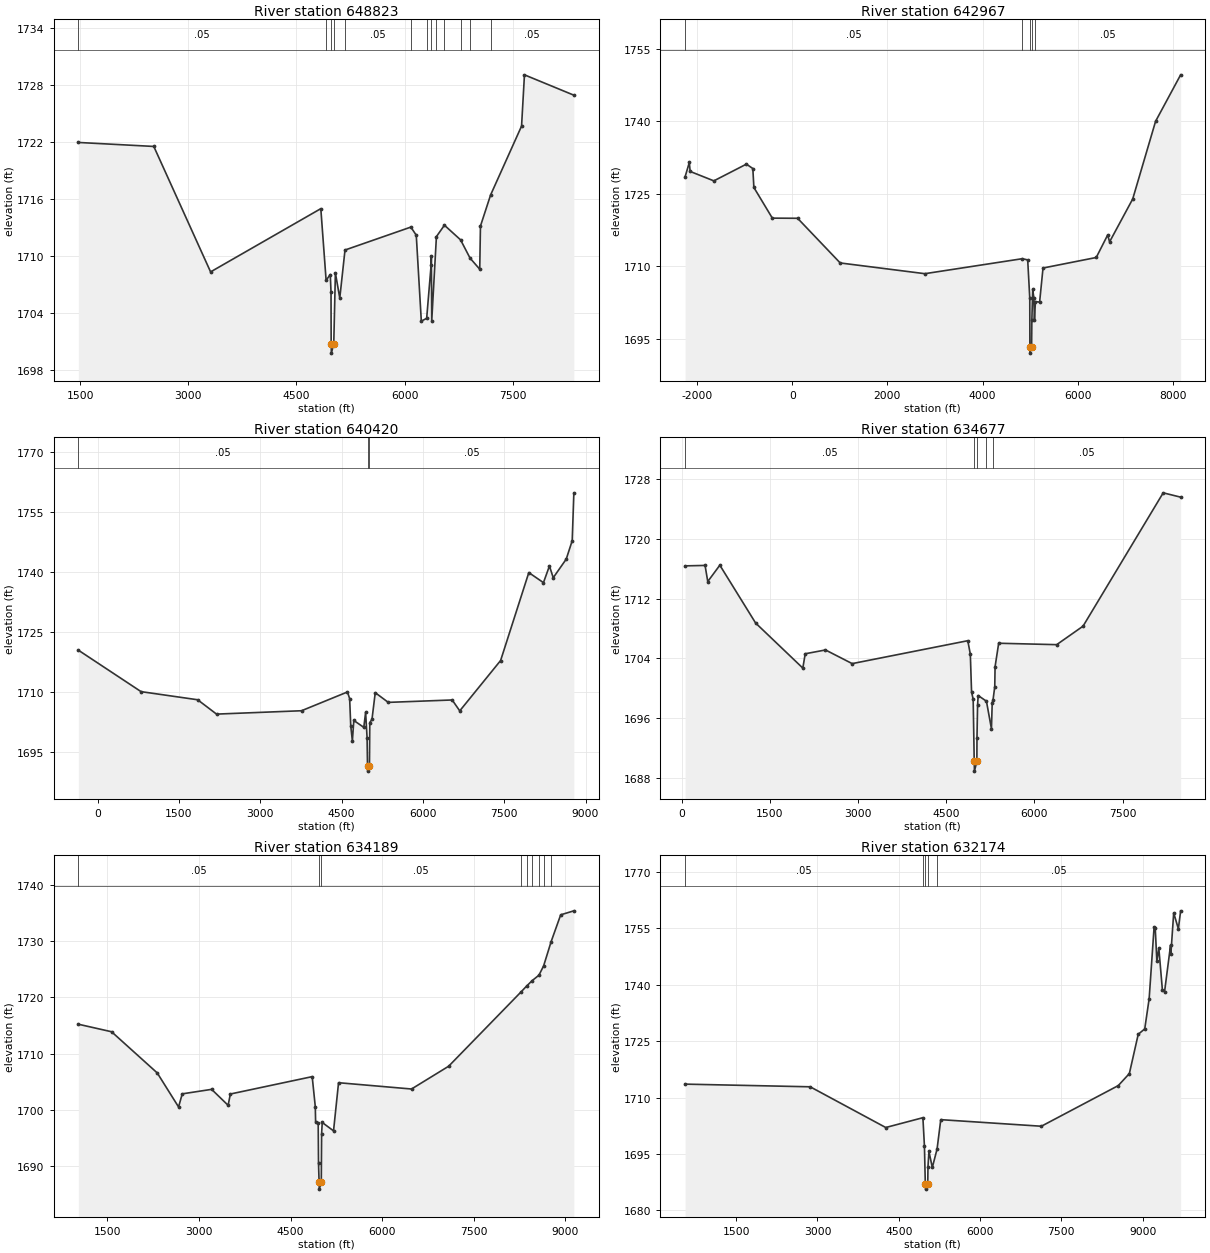
Type RM Length L Ch R = 1,648823,5856,5856,5856
BEGIN DESCRIPTION:
Mapping XS 02894f41
END DESCRIPTION:
XS GIS Cut Line= 4
      1507380.32      6930594.31      1508040.03      6929170.72
      1508369.90      6927087.39      1508265.73      6923893.00
#Sta/Elev= 30
  1474.3 1721.93  2521.4 1721.51  3309.3 1708.32  4838.4 1714.97  4911.8 1707.44
  4969.7 1708.04  4979.9 1706.17  4982.0 1700.78  4985.0 1699.78  5018.0 1700.78
  5040.6 1708.21  5101.4 1705.57  5173.9 1710.62  6087.0 1713.03  6162.5 1712.18
  6232.6 1703.14  6306.8 1703.44  6368.4 1709.02  6372.2 1709.99  6377.2 1703.18
  6442.0 1712.03  6553.1 1713.23  6777.1 1711.69  6908.6 1709.77  7043.0 1708.60
  7053.0 1713.14  7193.8 1716.41  7623.3 1723.65  7663.3 1729.04  8348.7 1726.90
#Mann=13,-1,0
  1474.3    0.05       0  4911.8     0.1       0  4982.0    0.07       0
  5018.0     0.1       0  5173.9    0.05       0  6087.0     0.1       0
  6306.8    0.05       0  6368.4     0.1       0  6442.0    0.05       0
  6553.1    0.12       0  6777.1    0.05       0  6908.6    0.12       0
  7193.8    0.05       0
Bank Sta=4982,5018
Exp/Cntr=0.3,0.1

Type RM Length L Ch R = 1,642967,2547,2547,2547
BEGIN DESCRIPTION:
Clear Fork Brazos Rv 150.0
END DESCRIPTION:
XS GIS Cut Line= 3
      1507746.65      6933349.16      1510742.72      6926596.82
      1511623.76      6923701.17
#Sta/Elev= 30
 -2251.5 1728.50 -2162.7 1731.46 -2145.5 1729.61 -1647.3 1727.66  -962.9 1731.12
  -828.0 1730.21  -806.1 1726.29  -418.2 1719.95   112.8 1719.92  1007.9 1710.68
  2787.2 1708.46  4834.5 1711.56  4948.4 1711.31  4992.2 1703.34  4994.2 1693.33
  4997.2 1692.03  5030.2 1693.33  5035.9 1698.88  5053.7 1705.19  5076.9 1703.52
  5090.6 1698.95  5110.3 1702.69  5198.7 1702.58  5270.3 1709.63  6388.8 1711.81
  6629.2 1716.47  6669.0 1715.04  7155.1 1723.91  7636.0 1739.98  8162.4 1749.59
#Mann=5,-1,0
 -2251.5    0.05       0  4834.5     0.1       0  4994.2    0.07       0
  5030.2     0.1       0  5110.3    0.05       0
Bank Sta=4994.2,5030.2
Exp/Cntr=0.3,0.1

Type RM Length L Ch R = 1,640420,5743,5743,5743
BEGIN DESCRIPTION:
Mapping XS 115970a2
END DESCRIPTION:
XS GIS Cut Line= 5
      1512145.71      6932780.22      1512888.33      6928274.04
      1512786.90      6927194.26      1511918.84      6925753.29
      1511849.40      6923947.75
#Sta/Elev= 30
  -356.1 1720.39   801.5 1710.03  1845.4 1708.00  2193.4 1704.42  3760.9 1705.26
  4608.6 1709.95  4648.8 1708.28  4668.9 1701.53  4699.0 1697.73  4725.9 1702.83
  4910.0 1701.11  4943.3 1704.86  4970.2 1698.57  4978.1 1691.48  4981.1 1690.18
  5014.1 1691.48  5020.4 1702.31  5060.6 1703.09  5120.9 1709.77  5361.1 1707.35
  6540.2 1707.95  6679.6 1705.23  7433.3 1717.80  7953.6 1739.76  8223.8 1737.25
  8333.9 1741.41  8404.0 1738.48  8644.1 1743.13  8754.2 1747.74  8784.5 1759.68
#Mann=3,-1,0
  -356.1    0.05       0  4978.1    0.05       0  5014.1    0.05       0
Bank Sta=4978.1,5014.1
Exp/Cntr=0.3,0.1

Type RM Length L Ch R = 1,634677,488,488,488
BEGIN DESCRIPTION:
Mapping XS cf996e9b
END DESCRIPTION:
XS GIS Cut Line= 4
      1513470.49      6931485.81      1513244.82      6931173.34
      1513244.82      6930426.81      1514842.04      6923308.78
#Sta/Elev= 30
    60.7 1716.38   400.2 1716.44   446.1 1714.28   651.5 1716.47  1260.0 1708.72
  2062.6 1702.68  2103.6 1704.60  2448.2 1705.11  2902.0 1703.28  4867.9 1706.35
  4911.2 1704.55  4932.2 1699.48  4959.7 1698.50  4977.5 1690.17  4981.3 1688.87
  5022.5 1690.17  5024.4 1693.33  5034.7 1697.78  5044.9 1699.00  5185.2 1698.24
  5270.4 1694.55  5283.5 1698.04  5297.0 1698.40  5326.8 1700.18  5332.0 1702.86
  5393.4 1706.01  6379.9 1705.82  6828.2 1708.30  8191.3 1726.17  8487.7 1725.59
#Mann=5,-1,0
    60.7    0.05       0  4977.5   0.035       0  5022.5    0.05       0
  5185.2     0.1       0  5297.0    0.05       0
Bank Sta=4977.5,5022.5
Exp/Cntr=0.3,0.1

Type RM Length L Ch R = 1,634189,2015,2015,2015
BEGIN DESCRIPTION:
Mapping XS c2ac677d
END DESCRIPTION:
XS GIS Cut Line= 3
      1513574.68      6930982.32      1513592.04      6930357.37
      1515310.41      6923067.34
#Sta/Elev= 30
  1023.1 1715.21  1567.6 1713.87  2315.5 1706.55  2664.8 1700.50  2725.2 1702.83
  3206.3 1703.63  3476.4 1700.79  3513.0 1702.80  4853.1 1705.89  4903.9 1700.54
  4909.0 1697.85  4951.4 1697.64  4956.5 1690.50  4966.0 1687.19  4969.0 1685.89
  5002.0 1687.19  5007.3 1695.77  5017.5 1697.74  5202.5 1696.25  5284.7 1704.81
  6479.6 1703.69  7087.7 1707.74  8266.8 1720.88  8366.8 1722.02  8455.7 1722.96
  8566.6 1723.93  8642.9 1725.58  8766.5 1729.91  8922.6 1734.66  9138.1 1735.37
#Mann=9,-1,0
  1023.1    0.05       0  4966.0    0.05       0  5002.0    0.05       0
  8266.8    0.12       0  8366.8    0.05       0  8455.7    0.12       0
  8566.6    0.05       0  8642.9    0.12       0  8766.5    0.05       0
Bank Sta=4966,5002
Exp/Cntr=0.3,0.1

Type RM Length L Ch R = 1,632174,2991,2991,2991
BEGIN DESCRIPTION:
Mapping XS f3615e49
END DESCRIPTION:
XS GIS Cut Line= 4
      1515090.39      6932021.06      1516027.90      6928843.94
      1515194.57      6925692.90      1515663.32      6923166.85
#Sta/Elev= 30
   559.0 1713.56  2866.4 1712.85  4260.4 1702.02  4945.7 1704.63  4974.1 1697.05
  4990.3 1686.93  4994.0 1685.63  5035.3 1686.93  5039.1 1691.51  5056.9 1695.64
  5119.5 1691.40  5207.1 1696.29  5275.3 1704.11  7130.9 1702.36  8549.6 1713.17
  8754.2 1716.37  8917.7 1726.82  9037.8 1728.25  9119.2 1736.26  9210.7 1755.39
  9231.1 1755.17  9261.6 1746.28  9297.7 1749.73  9363.3 1738.65  9403.4 1738.12
  9514.1 1750.50  9519.2 1748.06  9572.0 1759.10  9658.3 1754.88  9700.1 1759.66
#Mann=5,-1,0
   559.0    0.05       0  4945.7     0.1       0  4990.3    0.07       0
  5035.3     0.1       0  5207.1    0.05       0
Bank Sta=4990.3,5035.3
Exp/Cntr=0.3,0.1

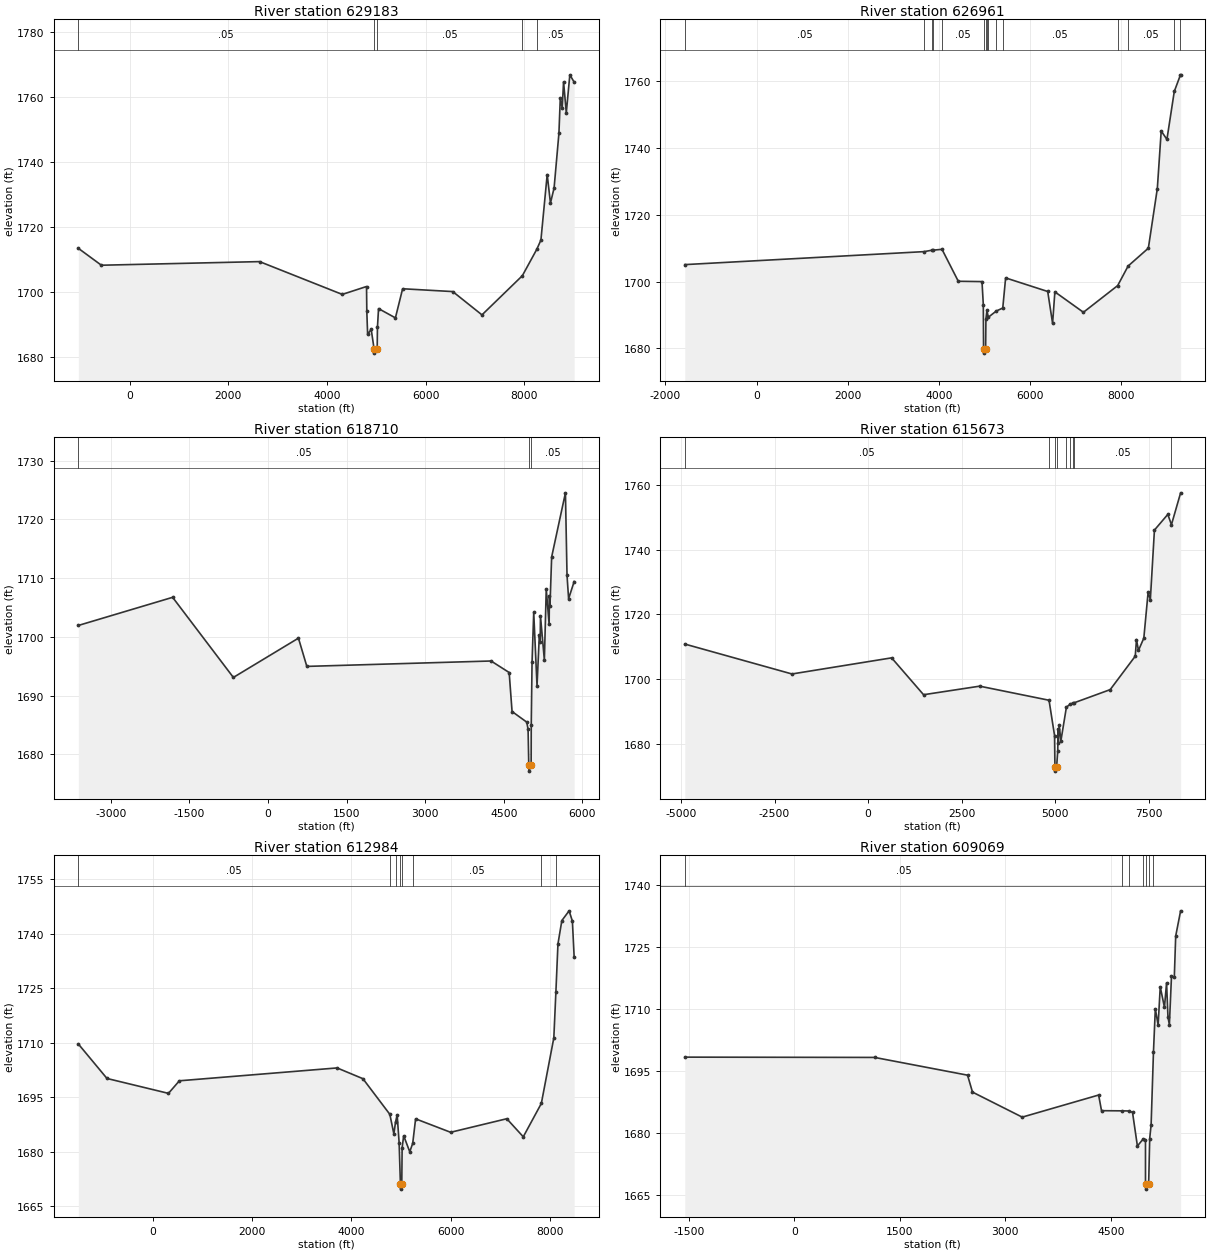
Type RM Length L Ch R = 1,629183,2222,2222,2222
BEGIN DESCRIPTION:
Mapping XS f19cea20
END DESCRIPTION:
XS GIS Cut Line= 3
      1519705.40      6932412.82      1519346.04      6929033.64
      1516289.17      6923116.43
#Sta/Elev= 30
 -1044.1 1713.47  -576.7 1708.28  2632.5 1709.39  4309.9 1699.32  4802.4 1701.75
  4808.0 1694.13  4824.6 1687.04  4896.6 1688.63  4955.7 1682.60  4960.9 1681.30
  5018.7 1682.60  5023.9 1689.23  5046.0 1694.97  5388.2 1692.12  5534.6 1701.06
  6551.8 1700.19  7144.2 1693.04  7963.3 1705.06  8255.3 1713.14  8340.0 1716.00
  8467.2 1736.10  8533.7 1727.37  8607.3 1731.99  8705.2 1748.76  8733.0 1759.49
  8771.7 1756.58  8799.5 1764.58  8854.7 1755.06  8926.7 1766.72  9014.3 1764.48
#Mann=5,-1,0
 -1044.1    0.05       0  4955.7    0.05       0  5018.7    0.05       0
  7963.3    0.12       0  8255.3    0.05       0
Bank Sta=4955.7,5018.7
Exp/Cntr=0.3,0.1

Type RM Length L Ch R = 1,626961,8251,8251,8251
BEGIN DESCRIPTION:
Mapping XS 2b30422f
END DESCRIPTION:
XS GIS Cut Line= 5
      1522179.35      6931414.51      1521507.61      6927884.52
      1520168.53      6925771.02      1518632.07      6924494.98
      1517173.76      6922125.22
#Sta/Elev= 30
 -1575.1 1705.11  3674.2 1709.00  3851.3 1709.44  3870.8 1709.44  4066.2 1709.69
  4423.6 1700.12  4943.5 1700.02  4972.2 1693.12  4977.9 1679.90  4981.7 1678.60
  5022.9 1679.90  5029.5 1688.84  5051.4 1691.38  5082.1 1689.35  5257.6 1691.21
  5398.9 1692.11  5461.8 1701.13  6384.9 1697.06  6491.7 1687.52  6541.9 1696.95
  7167.9 1690.83  7919.5 1698.83  8148.1 1704.68  8592.2 1710.03  8789.0 1727.89
  8874.1 1745.13  8999.6 1742.61  9160.9 1756.97  9296.9 1761.95  9300.0 1761.95
#Mann=15,-1,0
 -1575.1    0.05       0  3674.2     0.1       0  3851.3    0.05       0
  3870.8     0.1       0  4066.2    0.05       0  4977.9    0.05       0
  5022.9    0.05       0  5051.4    0.12       0  5082.1    0.05       0
  5257.6    0.12       0  5398.9    0.05       0  7919.5    0.12       0
  8148.1    0.05       0  9160.9    0.12       0  9296.9    0.05       0
Bank Sta=4977.9,5022.9
Exp/Cntr=0.3,0.1

Type RM Length L Ch R = 1,618710,3037,3037,3037
BEGIN DESCRIPTION:
Mapping XS d7c8b0c1
END DESCRIPTION:
XS GIS Cut Line= 5
      1523196.29      6928754.03      1523231.01      6927695.03
      1521546.98      6923580.44      1519307.40      6922781.83
      1518751.82      6921306.09
#Sta/Elev= 30
 -3616.7 1701.94 -1817.7 1706.73  -658.8 1693.09   582.9 1699.78   743.1 1694.97
  4258.0 1695.89  4603.4 1693.93  4658.5 1687.29  4939.3 1685.48  4964.2 1684.24
  4977.5 1678.14  4981.3 1677.14  5022.5 1678.14  5024.6 1684.99  5039.9 1695.70
  5071.9 1704.15  5134.8 1691.67  5178.8 1700.26  5195.2 1699.12  5200.6 1703.56
  5274.9 1696.05  5310.8 1708.13  5365.9 1702.13  5371.2 1706.95  5381.8 1705.20
  5413.9 1713.60  5676.9 1724.52  5707.1 1710.47  5737.4 1706.49  5843.3 1709.42
#Mann=3,-1,0
 -3616.7    0.05       0  4977.5    0.05       0  5022.5    0.05       0
Bank Sta=4977.5,5022.5
Exp/Cntr=0.3,0.1

Type RM Length L Ch R = 1,615673,2689,2689,2689
BEGIN DESCRIPTION:
Mapping XS f2fc6cd0
END DESCRIPTION:
XS GIS Cut Line= 3
      1523533.43      6932367.83      1523411.90      6927506.76
      1520095.91      6919815.74
#Sta/Elev= 30
 -4895.4 1710.79 -2034.7 1701.53   626.7 1706.52  1479.5 1695.11  2977.3 1697.76
  4829.3 1693.40  4976.8 1682.48  4986.7 1672.77  4990.5 1671.47  5031.7 1672.77
  5062.3 1677.81  5070.9 1684.55  5076.3 1680.04  5099.9 1685.63  5146.9 1680.91
  5293.0 1691.24  5400.9 1692.27  5476.8 1692.54  5508.7 1692.65  6462.4 1696.69
  7131.4 1707.04  7164.0 1712.18  7217.0 1708.81  7360.1 1712.63  7474.0 1726.75
  7534.3 1724.55  7643.2 1746.05  8000.5 1750.91  8097.5 1747.72  8342.6 1757.58
#Mann=9,-1,0
 -4895.4    0.05       0  4829.3     0.1       0  4986.7    0.07       0
  5031.7     0.1       0  5293.0     0.1       0  5400.9    0.05       0
  5476.8     0.1       0  5508.7    0.05       0  8097.5    0.12       0
Bank Sta=4986.7,5031.7
Exp/Cntr=0.3,0.1

Type RM Length L Ch R = 1,612984,3915,3915,3915
BEGIN DESCRIPTION:
Mapping XS 58148f4d
END DESCRIPTION:
XS GIS Cut Line= 2
      1525611.24      6929703.34      1522902.89      6920093.91
#Sta/Elev= 30
 -1499.3 1709.72  -922.3 1700.23   315.4 1696.13   535.1 1699.59  3711.4 1703.13
  4230.9 1700.17  4773.1 1690.36  4854.3 1684.96  4887.5 1688.24  4920.6 1690.18
  4959.8 1682.61  4986.4 1671.08  4988.7 1669.78  5013.4 1671.08  5020.5 1681.17
  5051.7 1684.47  5174.3 1680.05  5233.8 1682.39  5292.0 1689.12  5997.1 1685.42
  7127.8 1689.15  7459.9 1684.18  7823.5 1693.35  8075.1 1711.41  8116.3 1723.89
  8158.2 1737.25  8236.6 1743.68  8383.1 1746.36  8449.1 1743.52  8484.5 1733.61
#Mann=8,-1,0
 -1499.3    0.05       0  4773.1    0.12       0  4887.5     0.1       0
  4986.4    0.07       0  5013.4     0.1       0  5233.8    0.05       0
  7823.5    0.12       0  8116.3    0.05       0
Bank Sta=4986.4,5013.4
Exp/Cntr=0.3,0.1

Type RM Length L Ch R = 1,609069,2141,2141,2141
BEGIN DESCRIPTION:
Clear Fork Brazos Rv 144.0
END DESCRIPTION:
XS GIS Cut Line= 4
      1525366.65      6926890.96      1526114.61      6924298.52
      1525255.00      6920538.00      1525255.00      6920038.00
#Sta/Elev= 30
 -1561.0 1698.36  1140.0 1698.29  2462.7 1694.00  2532.8 1689.91  3240.6 1683.86
  4327.9 1689.20  4369.0 1685.42  4658.1 1685.38  4759.1 1685.35  4810.1 1685.02
  4879.6 1676.88  4962.4 1678.59  4994.7 1678.43  4994.9 1667.76  4998.6 1666.46
  5039.9 1667.76  5054.7 1678.69  5074.7 1681.97  5108.5 1699.72  5134.7 1710.03
  5174.7 1706.12  5204.7 1715.34  5264.7 1710.41  5294.7 1716.33  5314.7 1708.00
  5334.7 1706.22  5364.7 1717.92  5404.7 1717.62  5424.7 1727.64  5494.7 1733.72
#Mann=7,-1,0
 -1561.0    0.05       0  4658.1     0.1       0  4759.1    0.05       0
  4962.4     0.1       0  4994.9    0.07       0  5039.9     0.1       0
  5108.5    0.05       0
Bank Sta=4994.9,5039.9
Exp/Cntr=0.3,0.1

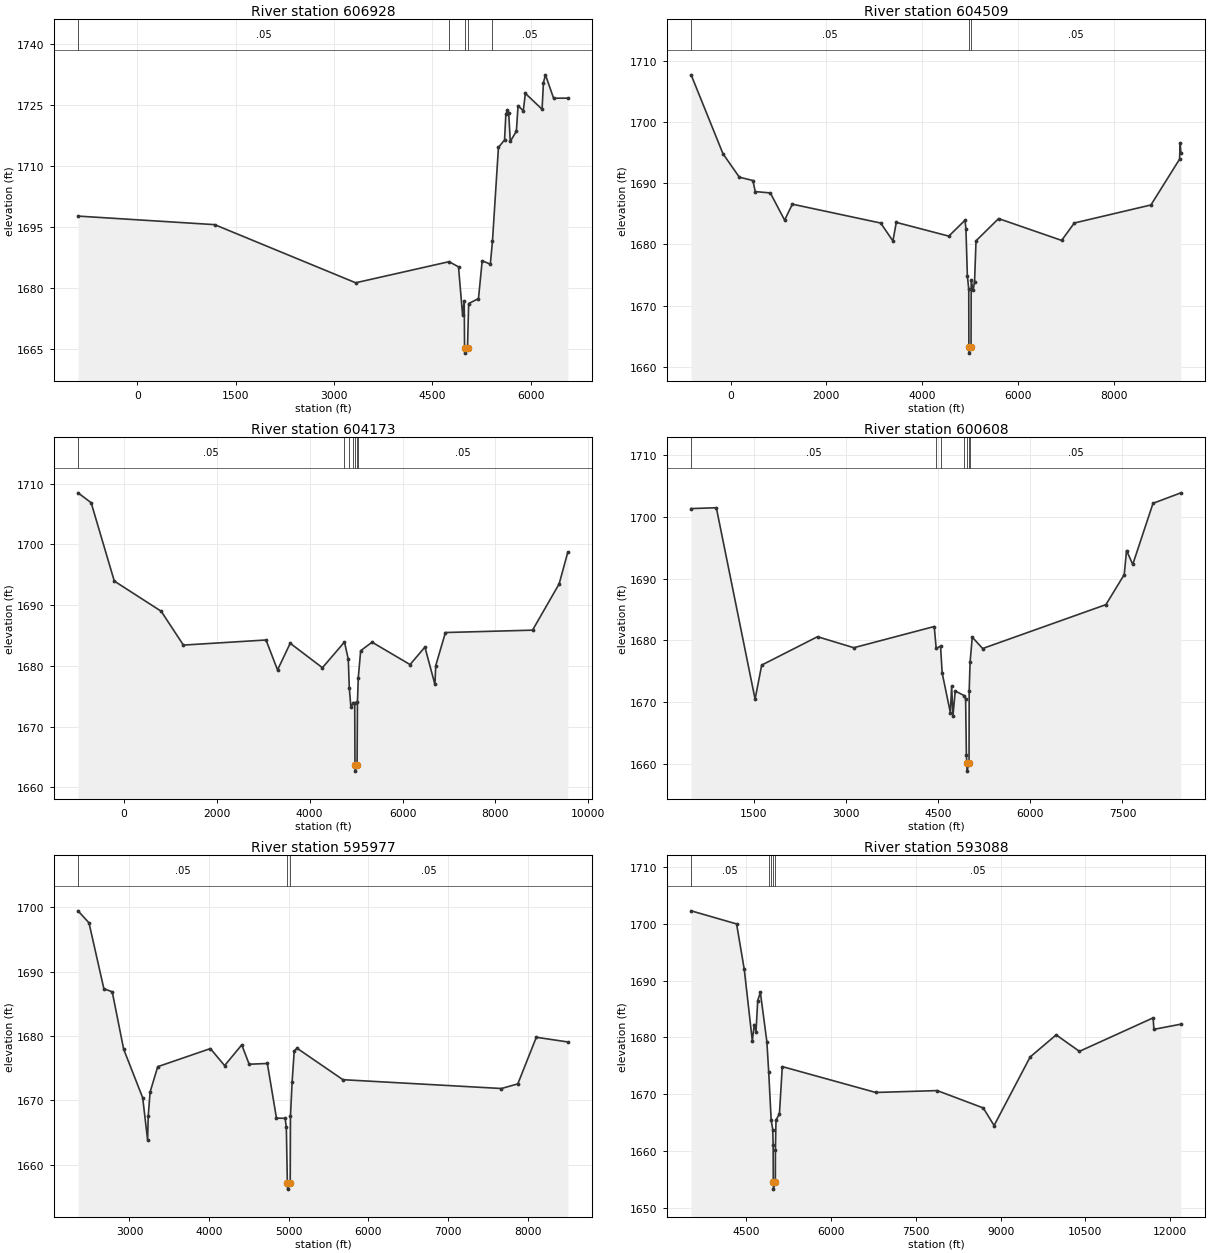
Type RM Length L Ch R = 1,606928,2419,2419,2419
BEGIN DESCRIPTION:
Mapping XS 0342b55d
END DESCRIPTION:
XS GIS Cut Line= 3
      1525874.46      6925875.35      1527799.72      6922338.22
      1526658.44      6919086.64
#Sta/Elev= 30
  -904.8 1697.69  1179.5 1695.59  3331.1 1681.31  4756.0 1686.49  4900.4 1685.22
  4962.4 1673.43  4987.8 1676.87  4992.6 1665.33  4996.4 1664.03  5037.6 1665.33
  5055.3 1676.21  5205.0 1677.42  5261.7 1686.72  5385.7 1685.88  5418.3 1691.47
  5509.7 1714.58  5602.6 1716.38  5623.0 1722.69  5644.9 1723.63  5666.1 1723.03
  5690.3 1716.02  5783.3 1718.55  5809.0 1724.83  5888.7 1723.54  5920.5 1727.83
  6175.6 1723.93  6196.0 1730.48  6227.0 1732.39  6351.0 1726.65  6568.4 1726.66
#Mann=5,-1,0
  -904.8    0.05       0  4756.0     0.1       0  4992.6    0.07       0
  5037.6     0.1       0  5418.3    0.05       0
Bank Sta=4992.6,5037.6
Exp/Cntr=0.3,0.1

Type RM Length L Ch R = 1,604509,336,336,336
BEGIN DESCRIPTION:
Mapping XS a9f59c11
END DESCRIPTION:
XS GIS Cut Line= 6
      1528479.45      6926099.93      1528798.21      6923199.15
      1529172.75      6922003.51      1529201.56      6919208.86
      1529885.66      6917084.76      1529359.83      6916203.23
#Sta/Elev= 30
  -826.9 1707.76  -161.0 1694.84   180.6 1691.01   463.8 1690.46   513.1 1688.65
   828.0 1688.43  1126.7 1683.98  1288.2 1686.59  3134.8 1683.50  3390.0 1680.57
  3460.2 1683.61  4558.3 1681.36  4895.7 1683.96  4915.8 1682.53  4945.9 1674.82
  4974.8 1672.66  4977.5 1663.21  4981.3 1662.21  5022.5 1663.21  5026.1 1674.13
  5066.2 1672.49  5096.3 1673.93  5126.4 1680.59  5597.9 1684.23  6915.0 1680.66
  7180.8 1683.51  8781.6 1686.46  9379.5 1693.95  9392.7 1696.55  9408.3 1694.99
#Mann=3,-1,0
  -826.9    0.05       0  4977.5    0.05       0  5022.5    0.05       0
Bank Sta=4977.5,5022.5
Exp/Cntr=0.3,0.1

Type RM Length L Ch R = 1,604173,3565,3565,3565
BEGIN DESCRIPTION:
Mapping XS bebd9566
END DESCRIPTION:
XS GIS Cut Line= 6
      1528726.01      6926109.78      1528798.21      6924826.96
      1529576.10      6921873.86      1529504.08      6919698.65
      1530138.42      6917265.30      1529349.59      6915996.99
#Sta/Elev= 30
  -982.3 1708.51  -700.1 1706.88  -201.9 1693.97   806.3 1689.00  1285.4 1683.42
  3063.2 1684.26  3310.9 1679.32  3583.5 1683.72  4276.8 1679.69  4751.6 1683.93
  4833.5 1681.07  4854.7 1676.41  4890.0 1673.17  4941.3 1673.95  4971.7 1673.93
  4977.5 1663.65  4981.3 1662.65  5022.5 1663.65  5030.7 1674.07  5048.8 1678.07
  5099.8 1682.49  5345.0 1683.90  6162.2 1680.21  6482.6 1683.09  6697.9 1676.93
  6715.2 1680.04  6923.8 1685.49  8798.3 1685.88  9370.9 1693.51  9557.8 1698.75
#Mann=7,-1,0
  -982.3    0.05       0  4751.6     0.1       0  4854.7    0.05       0
  4941.3     0.1       0  4977.5    0.07       0  5022.5     0.1       0
  5048.8    0.05       0
Bank Sta=4977.5,5022.5
Exp/Cntr=0.3,0.1

Type RM Length L Ch R = 1,600608,4631,4631,4631
BEGIN DESCRIPTION:
Mapping XS 5f017d27
END DESCRIPTION:
XS GIS Cut Line= 3
      1533195.86      6922298.78      1531481.46      6919347.41
      1529159.69      6915419.93
#Sta/Elev= 30
   476.2 1701.31   886.8 1701.45  1517.6 1670.49  1625.2 1676.00  2534.2 1680.59
  3125.4 1678.81  4434.7 1682.24  4466.8 1678.70  4537.5 1679.06  4564.3 1674.71
  4697.0 1668.33  4718.4 1672.56  4739.9 1667.81  4776.9 1671.81  4927.3 1671.04
  4945.8 1670.58  4958.3 1661.47  4965.5 1660.15  4968.5 1658.85  5001.5 1660.15
  5003.9 1671.80  5018.6 1676.47  5053.9 1680.51  5223.6 1678.68  7230.7 1685.78
  7529.1 1690.64  7566.1 1694.53  7667.5 1692.28  7997.2 1702.16  8451.8 1703.86
#Mann=7,-1,0
   476.2    0.05       0  4466.8     0.1       0  4537.5    0.05       0
  4927.3     0.1       0  4965.5    0.07       0  5001.5     0.1       0
  5018.6    0.05       0
Bank Sta=4965.5,5001.5
Exp/Cntr=0.3,0.1

Type RM Length L Ch R = 1,595977,2889,2889,2889
BEGIN DESCRIPTION:
Mapping XS ac20b5de
END DESCRIPTION:
XS GIS Cut Line= 3
      1534531.54      6921340.81      1533537.58      6917681.90
      1532831.72      6915434.67
#Sta/Elev= 30
  2355.0 1699.45  2492.6 1697.58  2679.2 1687.35  2784.2 1686.87  2927.8 1677.95
  3166.6 1670.41  3228.4 1663.82  3235.9 1667.56  3259.4 1671.30  3355.3 1675.24
  4015.9 1678.05  4194.6 1675.41  4409.7 1678.63  4502.9 1675.62  4731.0 1675.74
  4845.2 1667.25  4954.2 1667.22  4969.2 1665.80  4982.0 1657.22  4985.0 1656.22
  5018.0 1657.22  5021.1 1667.58  5041.8 1672.89  5068.4 1677.69  5103.1 1678.11
  5679.3 1673.22  7669.3 1671.85  7874.3 1672.57  8106.4 1679.81  8502.0 1679.08
#Mann=3,-1,0
  2355.0    0.05       0  4982.0    0.05       0  5018.0    0.05       0
Bank Sta=4982,5018
Exp/Cntr=0.3,0.1

Type RM Length L Ch R = 1,593088,4066,4066,4066
BEGIN DESCRIPTION:
Mapping XS 0403abc8
END DESCRIPTION:
XS GIS Cut Line= 3
      1536451.07      6921343.89      1535995.35      6918110.43
      1532392.90      6914095.65
#Sta/Elev= 30
  3528.5 1702.30  4332.3 1699.99  4468.1 1691.98  4610.5 1679.40  4645.3 1682.26
  4675.6 1681.02  4705.9 1686.47  4752.8 1687.92  4867.5 1679.25  4900.3 1673.87
  4943.6 1665.45  4971.4 1663.73  4978.6 1661.06  4981.5 1654.54  4984.5 1653.24
  5017.5 1654.54  5019.0 1660.18  5029.1 1665.43  5089.7 1666.49  5140.2 1674.84
  6792.6 1670.28  7879.4 1670.61  8693.4 1667.55  8884.8 1664.45  9522.5 1676.54
  9982.2 1680.43 10393.4 1677.53 11696.3 1683.43 11710.5 1681.41 12188.0 1682.32
#Mann=5,-1,0
  3528.5    0.05       0  4900.3     0.1       0  4943.6    0.05       0
  4981.5   0.035       0  5017.5    0.05       0
Bank Sta=4981.5,5017.5
Exp/Cntr=0.3,0.1

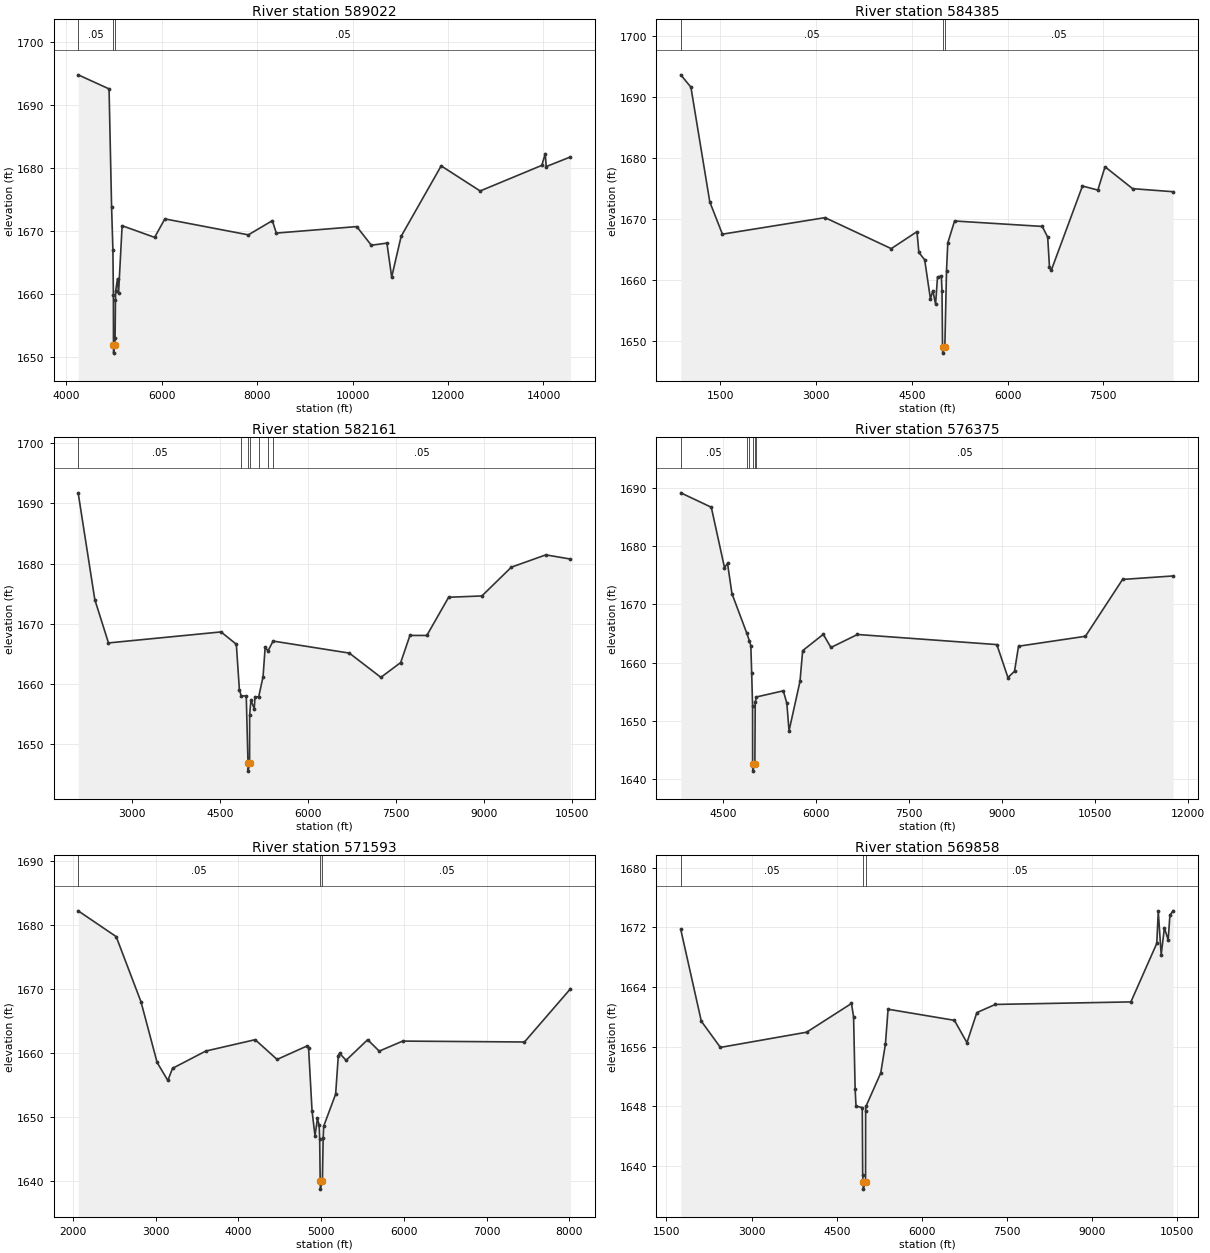
Type RM Length L Ch R = 1,589022,4637,4637,4637
BEGIN DESCRIPTION:
Mapping XS 74d5c278
END DESCRIPTION:
XS GIS Cut Line= 4
      1540357.30      6920410.76      1538794.83      6919521.02
      1536581.29      6918631.26      1532676.10      6913901.65
#Sta/Elev= 30
  4249.1 1694.81  4896.6 1692.58  4949.9 1673.80  4977.3 1667.07  4987.4 1659.82
  4989.2 1651.97  4991.5 1650.67  5016.2 1651.97  5022.8 1653.05  5030.6 1659.04
  5036.4 1660.58  5073.8 1662.49  5095.4 1660.14  5170.4 1670.88  5851.3 1669.03
  6065.9 1671.96  7815.7 1669.43  8318.3 1671.68  8401.6 1669.71 10087.2 1670.74
 10393.4 1667.78 10719.5 1668.12 10819.4 1662.74 11017.7 1669.20 11856.5 1680.37
 12673.3 1676.39 13965.7 1680.45 14037.4 1682.31 14058.2 1680.26 14566.3 1681.79
#Mann=3,-1,0
  4249.1    0.05       0  4989.2    0.05       0  5016.2    0.05       0
Bank Sta=4989.2,5016.2
Exp/Cntr=0.3,0.1

Type RM Length L Ch R = 1,584385,2224,2224,2224
BEGIN DESCRIPTION:
Mapping XS c52d7704
END DESCRIPTION:
XS GIS Cut Line= 4
      1540769.03      6918978.36      1539098.05      6918085.25
      1536548.30      6917782.73      1534329.96      6915405.94
#Sta/Elev= 30
   880.8 1693.60  1039.6 1691.58  1335.5 1672.77  1533.0 1667.48  3141.1 1670.19
  4178.3 1665.11  4581.6 1667.89  4611.3 1664.48  4702.0 1663.28  4792.6 1656.86
  4829.7 1658.24  4873.1 1656.03  4903.4 1660.48  4963.8 1660.59  4973.8 1658.17
  4982.0 1648.98  4985.0 1647.98  5018.0 1648.98  5044.3 1661.49  5064.5 1666.06
  5170.7 1669.64  6544.5 1668.75  6629.5 1666.99  6657.8 1662.02  6686.1 1661.57
  7174.2 1675.37  7415.0 1674.71  7527.9 1678.53  7959.7 1674.94  8594.3 1674.44
#Mann=3,-1,0
   880.8    0.05       0  4982.0    0.05       0  5018.0    0.05       0
Bank Sta=4982,5018
Exp/Cntr=0.3,0.1

Type RM Length L Ch R = 1,582161,5786,5786,5786
BEGIN DESCRIPTION:
Clear Fork Brazos Rv 141.0
END DESCRIPTION:
XS GIS Cut Line= 3
      1540805.01      6918738.01      1538305.00      6917238.00
      1535135.07      6912773.02
#Sta/Elev= 30
  2084.4 1691.75  2368.2 1674.00  2601.4 1666.80  4519.8 1668.63  4780.3 1666.58
  4832.7 1658.98  4864.6 1657.98  4949.4 1658.00  4979.4 1646.79  4981.6 1645.49
  5006.4 1646.79  5007.3 1654.75  5028.2 1657.27  5085.7 1655.88  5099.5 1657.85
  5161.6 1657.83  5236.1 1661.21  5271.7 1666.09  5320.2 1665.47  5406.5 1667.11
  6706.1 1665.11  7244.2 1661.08  7581.9 1663.54  7739.4 1668.05  8027.2 1668.04
  8398.7 1674.39  8965.8 1674.61  9467.7 1679.39 10055.7 1681.44 10475.7 1680.74
#Mann=7,-1,0
  2084.4    0.05       0  4864.6     0.1       0  4979.4    0.07       0
  5006.4     0.1       0  5161.6    0.05       0  5320.2     0.1       0
  5406.5    0.05       0
Bank Sta=4979.4,5006.4
Exp/Cntr=0.3,0.1

Type RM Length L Ch R = 1,576375,4782,4782,4782
BEGIN DESCRIPTION:
Mapping XS bee2ba9b
END DESCRIPTION:
XS GIS Cut Line= 3
      1542724.12      6917683.38      1541203.25      6915995.85
      1537765.73      6911495.82
#Sta/Elev= 30
  3820.9 1689.20  4312.8 1686.72  4525.3 1676.35  4574.6 1677.05  4645.6 1671.86
  4881.7 1665.14  4925.5 1663.78  4949.8 1662.91  4964.0 1658.15  4978.2 1652.52
  4979.0 1642.62  4982.0 1641.32  5015.0 1642.62  5020.8 1653.20  5041.1 1654.08
  5473.7 1655.14  5530.5 1652.98  5565.6 1648.25  5742.7 1656.78  5785.3 1662.05
  6117.9 1664.86  6240.5 1662.59  6668.5 1664.83  8915.0 1663.09  9093.7 1657.42
  9199.7 1658.50  9264.1 1662.81 10342.5 1664.52 10941.1 1674.30 11755.4 1674.90
#Mann=6,-1,0
  3820.9    0.05       0  4881.7     0.1       0  4925.5    0.05       0
  4979.0    0.07       0  5015.0    0.05       0  5041.1    0.05       0
Bank Sta=4979,5015
Exp/Cntr=0.3,0.1

Type RM Length L Ch R = 1,571593,1735,1735,1735
BEGIN DESCRIPTION:
Clear Fork Brazos Rv 139.0
END DESCRIPTION:
XS GIS Cut Line= 3
      1543805.03      6915638.04      1542122.93      6913250.46
      1539304.98      6912137.99
#Sta/Elev= 30
  2063.2 1682.18  2522.7 1678.15  2823.2 1667.93  3017.4 1658.47  3147.1 1655.65
  3203.8 1657.55  3605.3 1660.25  4202.7 1662.03  4467.5 1658.94  4833.3 1661.07
  4848.1 1660.73  4889.9 1650.92  4925.7 1646.98  4955.2 1649.71  4976.1 1648.66
  4982.3 1646.54  4988.4 1639.96  4990.6 1638.66  5015.4 1639.96  5024.6 1646.71
  5030.7 1648.50  5175.1 1653.52  5207.4 1659.53  5222.7 1659.91  5301.2 1658.80
  5562.1 1662.03  5701.9 1660.24  5985.7 1661.81  7457.4 1661.67  8013.4 1669.99
#Mann=3,-1,0
  2063.2    0.05       0  4988.4   0.035       0  5015.4    0.05       0
Bank Sta=4988.4,5015.4
Exp/Cntr=0.3,0.1

Type RM Length L Ch R = 1,569858,3093,3093,3093
BEGIN DESCRIPTION:
Mapping XS 43527efd
END DESCRIPTION:
XS GIS Cut Line= 4
      1545133.92      6915204.20      1543491.69      6912409.53
      1540380.13      6911041.02      1538400.47      6910588.91
#Sta/Elev= 30
  1752.7 1671.73  2114.7 1659.43  2450.6 1655.92  3970.3 1657.96  4759.4 1661.81
  4796.5 1660.02  4823.8 1650.32  4839.5 1648.05  4949.5 1647.85  4956.7 1638.87
  4962.5 1637.92  4966.3 1636.92  5007.5 1637.92  5008.7 1647.45  5014.1 1648.01
  5274.6 1652.49  5357.3 1656.37  5404.0 1661.04  6572.2 1659.55  6793.1 1656.56
  6967.5 1660.59  7292.8 1661.68  9680.8 1662.02 10136.7 1669.87 10162.9 1674.16
 10214.2 1668.34 10270.7 1671.94 10337.3 1670.34 10368.1 1673.65 10424.0 1674.23
#Mann=3,-1,0
  1752.7    0.05       0  4962.5    0.05       0  5007.5    0.05       0
Bank Sta=4962.5,5007.5
Exp/Cntr=0.3,0.1

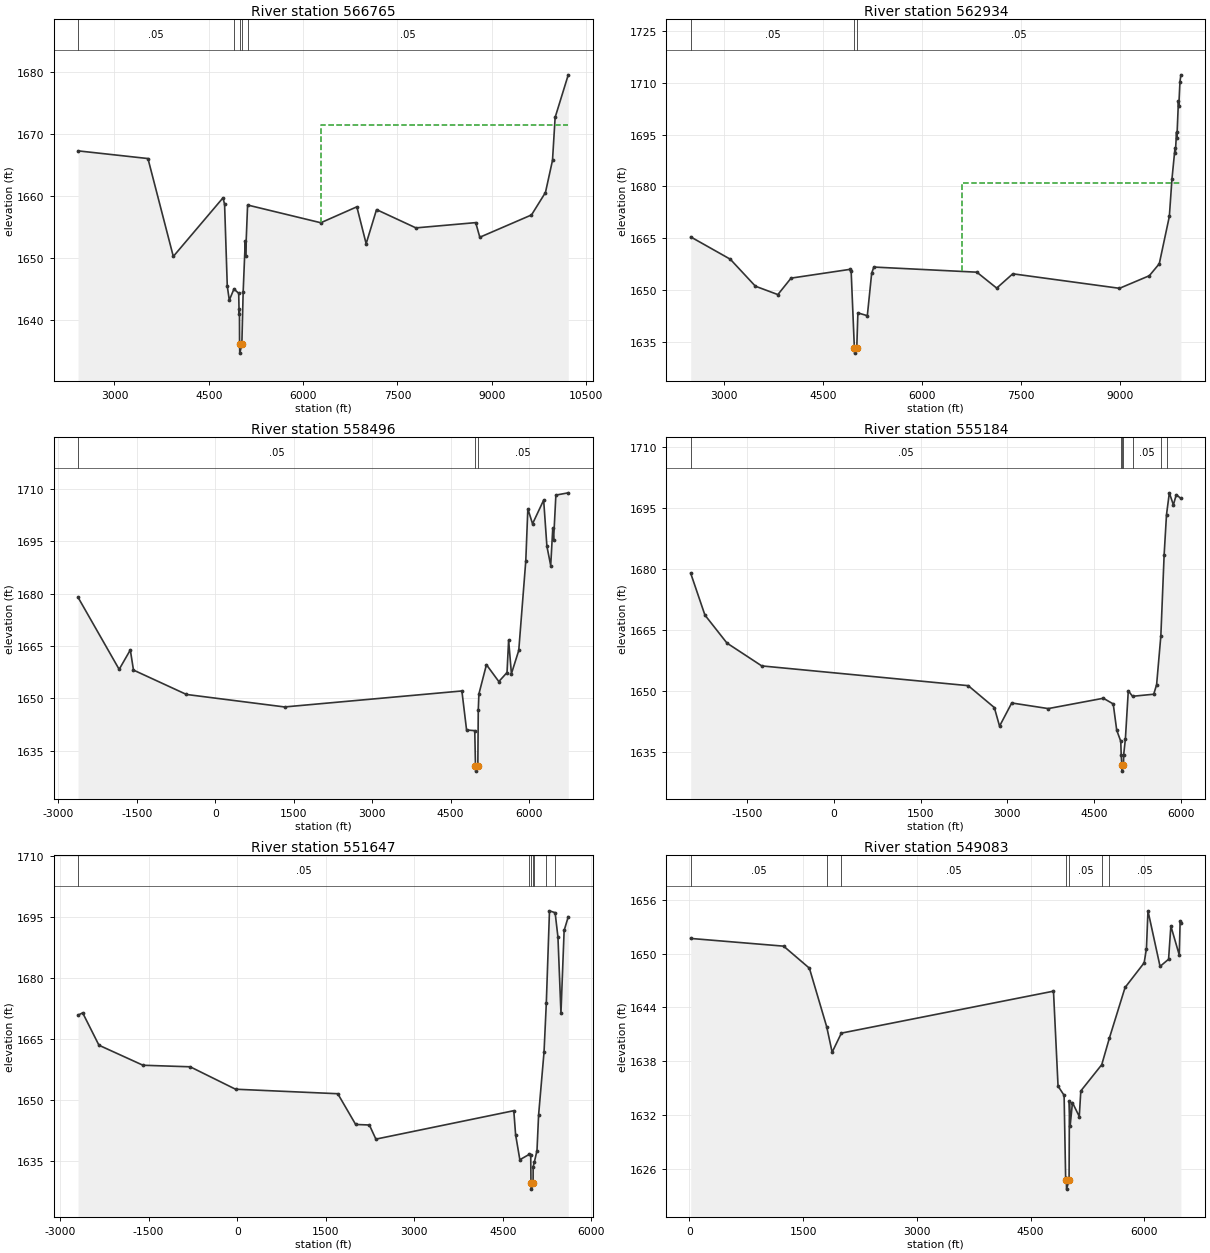
Type RM Length L Ch R = 1,566765,3831,3831,3831
BEGIN DESCRIPTION:
Clear Fork Brazos Rv 138.0
END DESCRIPTION:
XS GIS Cut Line= 3
      1546767.02      6914747.84      1545855.00      6912338.00
      1544355.00      6907338.00
#Sta/Elev= 30
  2420.4 1667.34  3532.2 1666.10  3935.4 1650.30  4726.5 1659.77  4751.1 1658.70
  4793.9 1645.52  4826.0 1643.25  4899.7 1645.04  4975.7 1644.36  4982.0 1641.04
  4987.3 1641.79  4989.5 1636.10  4992.5 1634.70  5025.5 1636.10  5046.6 1644.60
  5079.7 1652.76  5084.9 1650.39  5117.0 1658.60  6281.2 1655.74  6854.6 1658.31
  7002.5 1652.36  7167.8 1657.86  7794.2 1654.91  8745.1 1655.76  8810.4 1653.40
  9632.5 1657.00  9854.4 1660.62  9966.6 1665.81 10008.4 1672.74 10217.2 1679.61
#Mann=5,-1,0
  2420.4    0.05       0  4899.7     0.1       0  4989.5    0.07       0
  5025.5     0.1       0  5117.0    0.05       0
#XS Ineff=2,0
       0                 6278.50    0.00 1671.44
Permanent Ineff=
       F       F
Bank Sta=4989.5,5025.5
Exp/Cntr=0.3,0.1

Type RM Length L Ch R = 1,562934,4438,4438,4438
BEGIN DESCRIPTION:
Clear Fork Brazos Rv 137.0
END DESCRIPTION:
XS GIS Cut Line= 3
      1547605.00      6913938.02      1547605.00      6911438.00
      1545605.02      6906938.04
#Sta/Elev= 30
  2498.1 1665.43  3098.1 1658.98  3478.1 1651.19  3818.1 1648.77  4018.1 1653.52
  4918.1 1656.08  4928.1 1655.62  4977.2 1633.26  4980.2 1631.86  5013.2 1633.26
  5030.3 1643.48  5173.2 1642.67  5238.9 1654.92  5271.7 1656.72  6831.8 1655.24
  7132.7 1650.64  7376.2 1654.77  8992.4 1650.58  9444.5 1654.22  9594.9 1657.67
  9747.5 1671.35  9786.4 1682.01  9832.9 1691.05  9838.4 1689.70  9856.2 1695.63
  9861.7 1693.87  9884.9 1704.67  9890.4 1703.12  9908.2 1710.27  9922.5 1712.24
#Mann=3,-1,0
  2498.1    0.05       0  4977.2    0.04       0  5013.2    0.05       0
#XS Ineff=2,0
       0                 6607.10    0.00 1681.07
Permanent Ineff=
       F       F
Bank Sta=4977.2,5013.2
Exp/Cntr=0.3,0.1

Type RM Length L Ch R = 1,558496,3312,3312,3312
BEGIN DESCRIPTION:
Mapping XS ada4a363
END DESCRIPTION:
XS GIS Cut Line= 3
      1550252.17      6915770.62      1549453.25      6908975.01
      1548329.11      6906705.91
#Sta/Elev= 30
 -2625.0 1678.90 -1838.8 1658.32 -1625.5 1663.87 -1565.1 1658.12  -552.1 1651.15
  1324.6 1647.58  4715.5 1652.15  4805.2 1640.99  4961.8 1640.81  4975.4 1630.64
  4979.1 1629.24  5020.4 1630.64  5028.7 1646.60  5040.6 1651.28  5185.0 1659.66
  5421.8 1654.83  5578.7 1657.42  5609.1 1666.66  5662.8 1657.09  5803.0 1663.73
  5937.5 1689.35  5976.8 1704.21  6066.5 1699.92  6279.4 1706.69  6341.1 1693.53
  6414.0 1687.98  6453.2 1698.58  6468.4 1695.18  6513.0 1708.12  6749.7 1708.77
#Mann=3,-1,0
 -2625.0    0.05       0  4975.4    0.05       0  5020.4    0.05       0
Bank Sta=4975.4,5020.4
Exp/Cntr=0.3,0.1

Type RM Length L Ch R = 1,555184,3537,3537,3537
BEGIN DESCRIPTION:
Clear Fork Brazos Rv 135.0
END DESCRIPTION:
XS GIS Cut Line= 3
      1552539.59      6916093.32      1551955.00      6908638.00
      1551955.00      6907638.00
#Sta/Elev= 30
 -2477.6 1678.98 -2231.7 1668.71 -1850.4 1661.83 -1248.5 1656.22  2322.4 1651.37
  2773.8 1645.99  2864.1 1641.43  3074.7 1647.12  3706.6 1645.74  4659.6 1648.28
  4830.1 1646.88  4890.3 1640.45  4960.5 1637.70  4968.2 1634.30  4980.7 1631.78
  4982.9 1630.38  5007.7 1631.78  5010.6 1634.39  5040.6 1638.30  5090.6 1650.11
  5164.1 1648.76  5530.6 1649.27  5580.6 1651.63  5653.6 1663.57  5710.6 1683.50
  5751.5 1693.35  5800.6 1698.73  5870.6 1695.76  5920.6 1698.28  6000.6 1697.34
#Mann=7,-1,0
 -2477.6    0.05       0  4968.2     0.1       0  4980.7    0.07       0
  5007.7     0.1       0  5164.1    0.05       0  5653.6    0.12       0
  5751.5    0.05       0
Bank Sta=4980.7,5007.7
Exp/Cntr=0.3,0.1

Type RM Length L Ch R = 1,551647,2564,2564,2564
BEGIN DESCRIPTION:
Mapping XS 12294fab
END DESCRIPTION:
XS GIS Cut Line= 2
      1555786.59      6915391.71      1553974.08      6907287.52
#Sta/Elev= 30
 -2696.0 1670.84 -2617.7 1671.41 -2341.9 1663.44 -1595.8 1658.51  -796.5 1658.13
   -28.0 1652.61  1703.8 1651.50  2006.8 1643.93  2239.2 1643.80  2349.4 1640.32
  4685.7 1647.32  4716.4 1641.41  4788.1 1635.25  4947.6 1636.57  4972.6 1636.33
  4976.7 1629.41  4979.7 1628.01  5012.7 1629.41  5013.6 1633.57  5034.5 1634.70
  5078.7 1637.51  5105.8 1646.23  5198.0 1661.76  5236.4 1673.72  5290.3 1696.53
  5385.8 1696.07  5433.7 1690.06  5484.7 1671.34  5538.4 1691.69  5608.4 1695.07
#Mann=7,-1,0
 -2696.0    0.05       0  4947.6     0.1       0  4976.7    0.07       0
  5012.7     0.1       0  5034.5    0.05       0  5236.4    0.12       0
  5385.8    0.05       0
Bank Sta=4976.7,5012.7
Exp/Cntr=0.3,0.1

Type RM Length L Ch R = 1,549083,2639,2639,2639
BEGIN DESCRIPTION:
Mapping XS 536539a4
END DESCRIPTION:
XS GIS Cut Line= 4
      1556269.31      6912643.94      1556283.65      6911372.35
      1556326.87      6907540.52      1556168.41      6906186.41
#Sta/Elev= 30
    16.3 1651.68  1242.3 1650.82  1582.3 1648.36  1810.8 1641.82  1882.4 1638.99
  2004.1 1641.12  4802.5 1645.80  4862.6 1635.21  4942.6 1634.18  4962.6 1625.01
  4972.0 1624.72  4975.0 1623.72  5008.0 1624.72  5012.6 1633.52  5022.6 1630.80
  5052.6 1633.37  5142.7 1631.82  5162.9 1634.67  5439.1 1637.60  5539.7 1640.56
  5746.8 1646.21  5998.5 1648.96  6028.7 1650.54  6048.9 1654.76  6208.3 1648.56
  6320.7 1649.36  6350.9 1653.06  6461.7 1649.84  6473.2 1653.57  6483.4 1653.43
#Mann=7,-1,0
    16.3    0.05       0  1810.8    0.12       0  2004.1    0.05       0
  4972.0    0.05       0  5008.0    0.05       0  5439.1     0.1       0
  5539.7    0.05       0
Bank Sta=4972,5008
Exp/Cntr=0.3,0.1