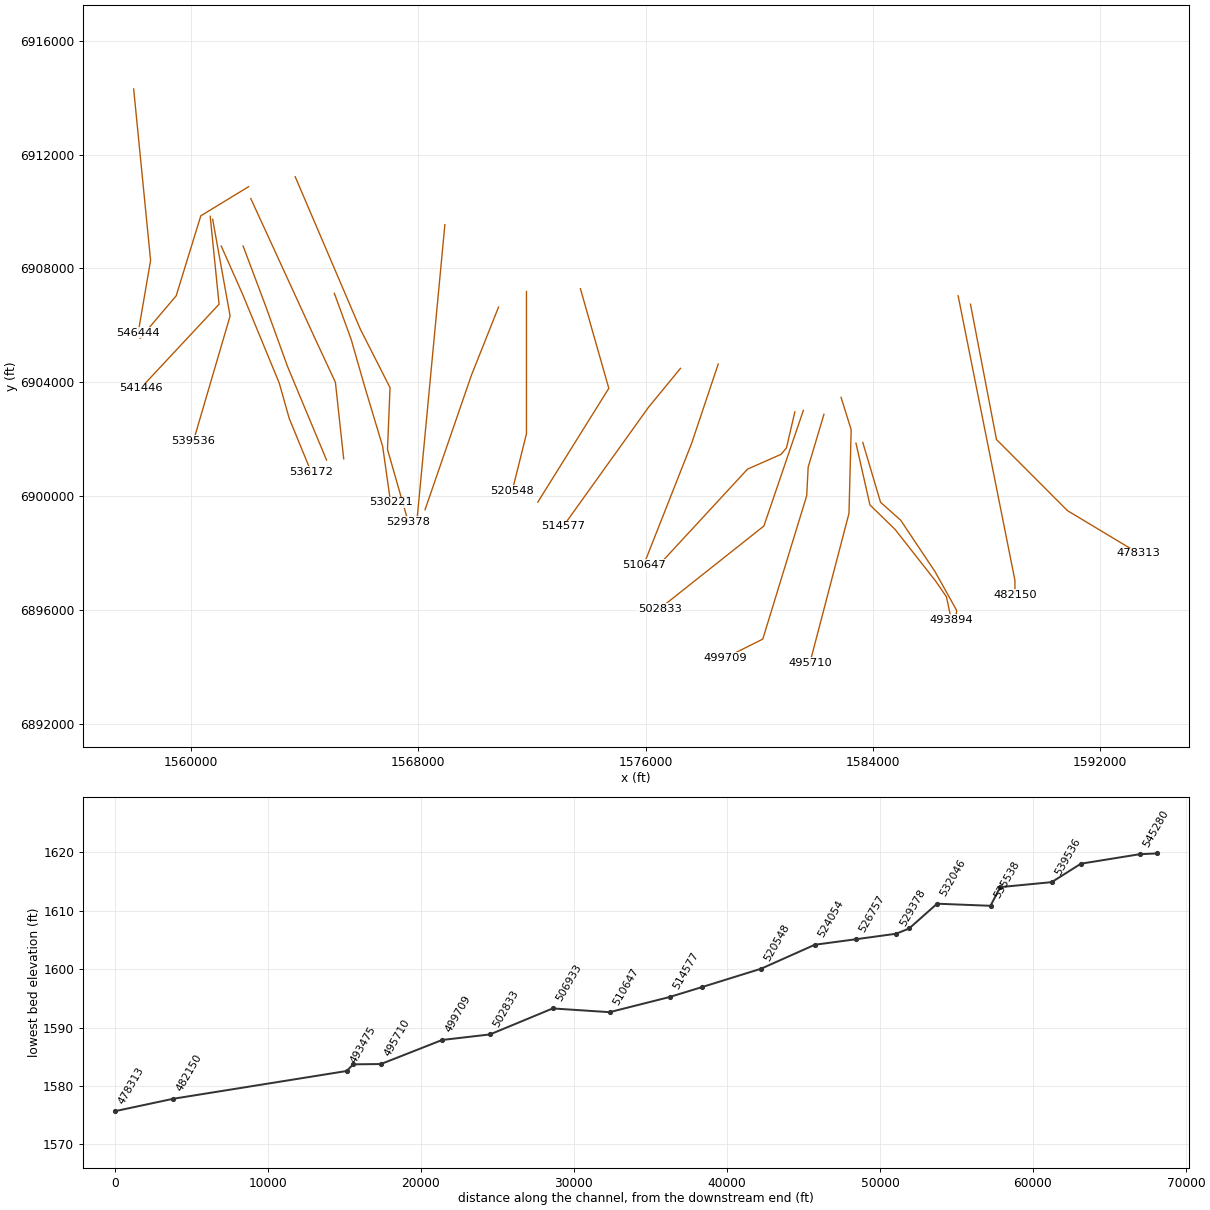
HEC-RAS study Clear Fork Brazos Rv.prj: Clear Fork Brazos Rv Base Level Engineering

--- Clear Fork Brazos Rv.g01 (geometry) --- (continued)

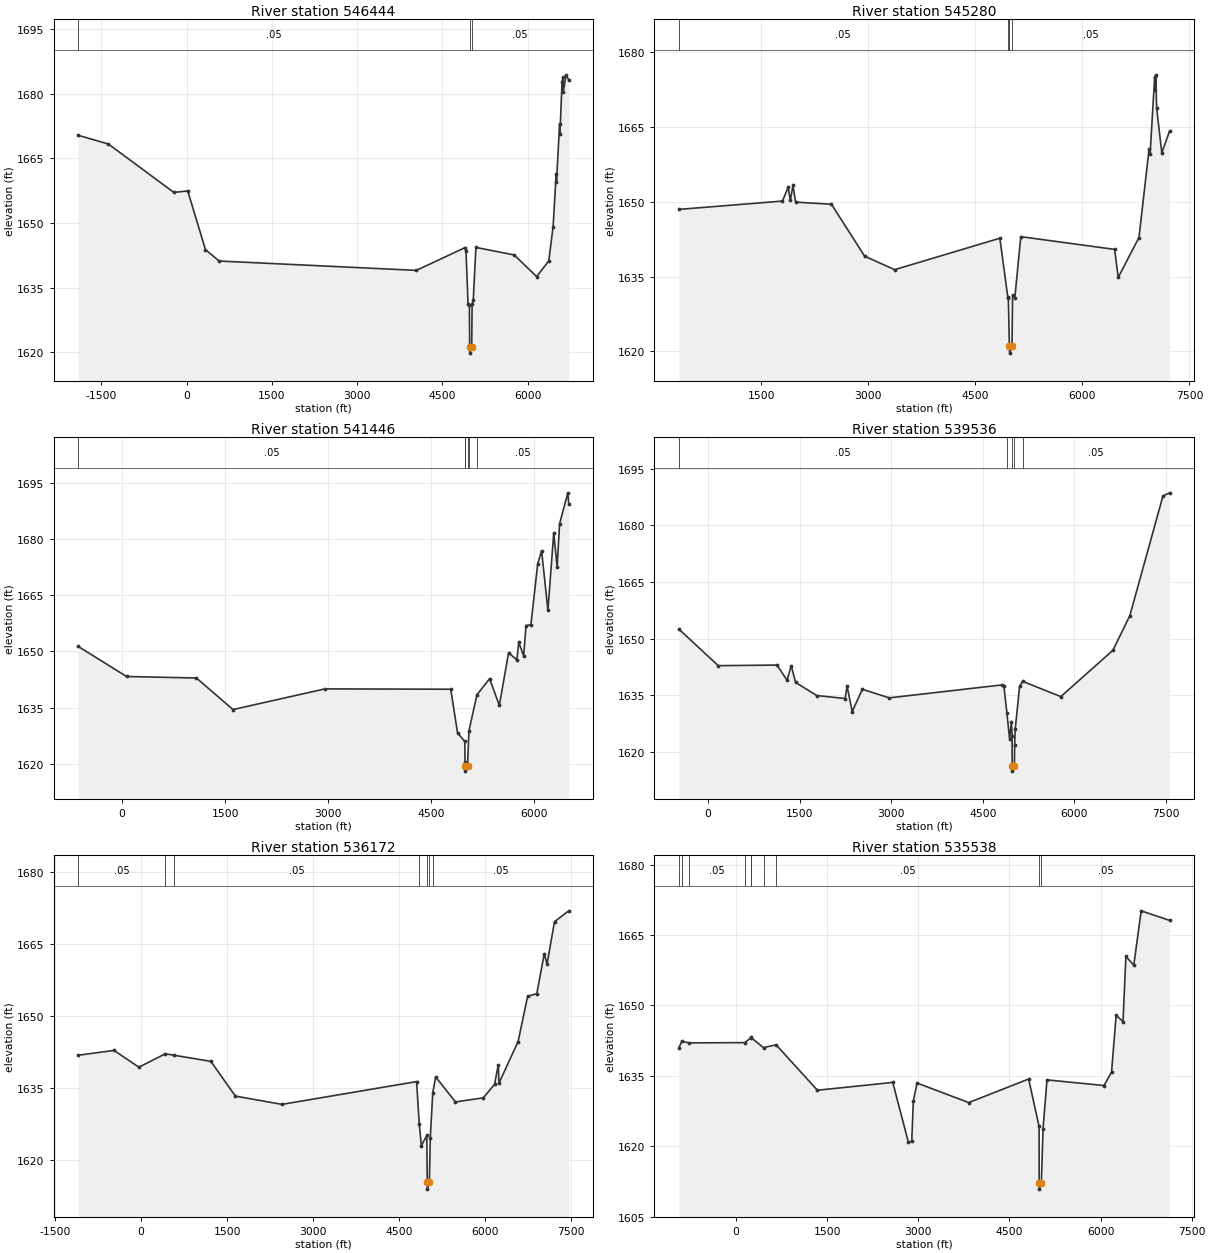
Type RM Length L Ch R = 1,546444,1164,1164,1164
BEGIN DESCRIPTION:
Mapping XS a53f048e
END DESCRIPTION:
XS GIS Cut Line= 3
      1557974.08      6914308.35      1558570.44      6908282.31
      1558133.14      6905741.84
#Sta/Elev= 30
 -1911.5 1670.33 -1378.6 1668.31  -227.4 1657.09    18.2 1657.42   329.7 1643.81
   570.9 1641.17  4040.4 1639.00  4899.2 1644.30  4913.7 1643.50  4950.0 1631.26
  4973.6 1631.02  4978.2 1621.21  4981.2 1619.81  5014.2 1621.21  5021.0 1631.23
  5041.3 1632.19  5088.3 1644.32  5761.7 1642.58  6157.5 1637.55  6370.6 1641.23
  6446.1 1649.14  6501.0 1661.41  6506.0 1659.51  6560.9 1673.00  6566.0 1670.58
  6603.9 1682.71  6620.8 1683.83  6625.9 1680.38  6675.0 1684.35  6721.8 1683.16
#Mann=3,-1,0
 -1911.5    0.05       0  4978.2    0.05       0  5014.2    0.05       0
Bank Sta=4978.2,5014.2
Exp/Cntr=0.3,0.1

Type RM Length L Ch R = 1,545280,3834,3834,3834
BEGIN DESCRIPTION:
Mapping XS 12989441
END DESCRIPTION:
XS GIS Cut Line= 4
      1562023.02      6910874.82      1560338.98      6909850.51
      1559470.93      6907038.01      1558203.59      6905544.97
#Sta/Elev= 30
   348.2 1648.44  1799.0 1650.10  1879.2 1652.90  1909.4 1650.24  1946.2 1653.27
  1983.0 1649.89  2484.8 1649.47  2949.8 1639.08  3370.3 1636.37  4844.1 1642.67
  4954.1 1630.99  4962.6 1630.62  4977.3 1621.31  4978.0 1621.07  4981.0 1619.67
  5014.0 1621.07  5022.0 1631.23  5053.4 1630.71  5137.1 1642.98  6451.9 1640.43
  6501.3 1634.82  6792.4 1642.81  6934.1 1660.51  6948.4 1659.50  7012.1 1674.91
  7019.8 1672.30  7026.3 1675.37  7040.6 1668.64  7112.1 1659.75  7221.1 1664.14
#Mann=5,-1,0
   348.2    0.05       0  4954.1     0.1       0  4977.3    0.05       0
  4978.0    0.05       0  5014.0    0.05       0
Bank Sta=4978,5014
Exp/Cntr=0.3,0.1

Type RM Length L Ch R = 1,541446,1910,1910,1910
BEGIN DESCRIPTION:
Mapping XS 58e1bcab
END DESCRIPTION:
XS GIS Cut Line= 3
      1560668.84      6909833.18      1560981.34      6906742.87
      1558221.67      6903792.27
#Sta/Elev= 30
  -640.1 1651.37    65.4 1643.32  1083.8 1642.91  1616.5 1634.49  2954.9 1640.01
  4787.2 1639.92  4886.4 1628.26  4992.4 1625.97  4995.4 1620.54  4996.0 1619.45
  4999.0 1618.05  5032.0 1619.45  5052.1 1628.78  5168.3 1638.42  5353.4 1642.74
  5495.0 1635.60  5629.4 1649.67  5749.6 1647.74  5777.9 1652.43  5848.7 1648.88
  5883.9 1656.92  5954.7 1657.14  6053.9 1673.42  6110.6 1676.90  6202.4 1661.00
  6287.4 1681.68  6336.7 1672.61  6372.4 1684.11  6492.6 1692.36  6506.0 1689.35
#Mann=6,-1,0
  -640.1    0.05       0  4995.4     0.1       0  4996.0    0.07       0
  5032.0     0.1       0  5052.1    0.12       0  5168.3    0.05       0
Bank Sta=4996,5032
Exp/Cntr=0.3,0.1

Type RM Length L Ch R = 1,539536,3364,3364,3364
BEGIN DESCRIPTION:
Mapping XS c7470c86
END DESCRIPTION:
XS GIS Cut Line= 3
      1560755.64      6909729.01      1561369.92      6906329.18
      1560078.24      6901933.30
#Sta/Elev= 30
  -478.3 1652.50   166.4 1642.83  1128.3 1642.99  1292.9 1638.98  1362.0 1642.81
  1433.2 1638.39  1778.7 1634.92  2243.5 1634.13  2276.6 1637.39  2360.7 1630.67
  2526.3 1636.58  2967.6 1634.30  4812.2 1637.73  4843.5 1637.53  4895.1 1630.17
  4937.3 1623.47  4968.6 1628.02  4979.0 1624.23  4980.6 1616.29  4983.6 1614.89
  5016.6 1616.29  5020.7 1621.77  5029.7 1625.97  5101.7 1637.33  5150.3 1638.68
  5777.4 1634.63  6630.4 1646.91  6907.2 1656.07  7450.0 1687.79  7558.3 1688.62
#Mann=5,-1,0
  -478.3    0.05       0  4895.1     0.1       0  4980.6    0.07       0
  5016.6     0.1       0  5150.3    0.05       0
Bank Sta=4980.6,5016.6
Exp/Cntr=0.3,0.1

Type RM Length L Ch R = 1,536172,634,634,634
BEGIN DESCRIPTION:
Mapping XS 9872ec2c
END DESCRIPTION:
XS GIS Cut Line= 5
      1561057.43      6908787.48      1561807.42      6907100.01
      1563099.08      6903975.01      1563453.25      6902725.01
      1564223.47      6900851.51
#Sta/Elev= 30
 -1098.7 1641.90  -473.4 1642.91   -38.4 1639.42   421.7 1642.21   580.8 1641.89
  1215.4 1640.63  1643.8 1633.40  2455.3 1631.68  4801.8 1636.42  4848.3 1627.64
  4885.0 1623.09  4980.1 1625.22  4987.5 1615.44  4990.5 1614.04  5023.5 1615.44
  5040.9 1624.78  5083.2 1634.01  5134.4 1637.39  5479.4 1632.19  5965.9 1633.04
  6161.2 1635.87  6225.4 1639.89  6238.5 1636.12  6571.4 1644.76  6737.0 1654.17
  6897.0 1654.72  7027.6 1663.05  7075.5 1660.90  7206.1 1669.71  7454.2 1671.96
#Mann=7,-1,0
 -1098.7    0.05       0   421.7   0.075       0   580.8    0.05       0
  4848.3     0.1       0  4987.5    0.07       0  5023.5     0.1       0
  5083.2    0.05       0
Bank Sta=4987.5,5023.5
Exp/Cntr=0.3,0.1

Type RM Length L Ch R = 1,535538,3492,3492,3492
BEGIN DESCRIPTION:
Mapping XS 37dc8d4d
END DESCRIPTION:
XS GIS Cut Line= 4
      1561828.24      6908787.55      1562619.92      6906683.35
      1563390.75      6904558.35      1564765.75      6901266.68
#Sta/Elev= 30
  -939.5 1640.95  -892.4 1642.32  -771.4 1642.00   143.0 1642.06   243.4 1643.05
   246.5 1643.15   453.6 1640.98   660.6 1641.60  1339.6 1631.91  2580.3 1633.58
  2837.4 1620.85  2893.3 1621.05  2918.6 1629.57  2979.8 1633.45  3830.9 1629.28
  4816.9 1634.30  4989.0 1624.19  4990.4 1612.24  4993.4 1610.84  5026.4 1612.24
  5054.3 1623.74  5118.9 1634.12  6057.3 1632.91  6181.4 1635.78  6257.2 1647.89
  6370.1 1646.54  6417.7 1660.41  6547.6 1658.58  6669.1 1670.14  7136.5 1668.10
#Mann=10,-1,0
  -939.5    0.05       0  -892.4   0.075       0  -771.4    0.05       0
   143.0     0.1       0   243.4   0.075       0   246.5     0.1       0
   453.6   0.075       0   660.6    0.05       0  4990.4    0.03       0
  5026.4    0.05       0
Bank Sta=4990.4,5026.4
Exp/Cntr=0.3,0.1

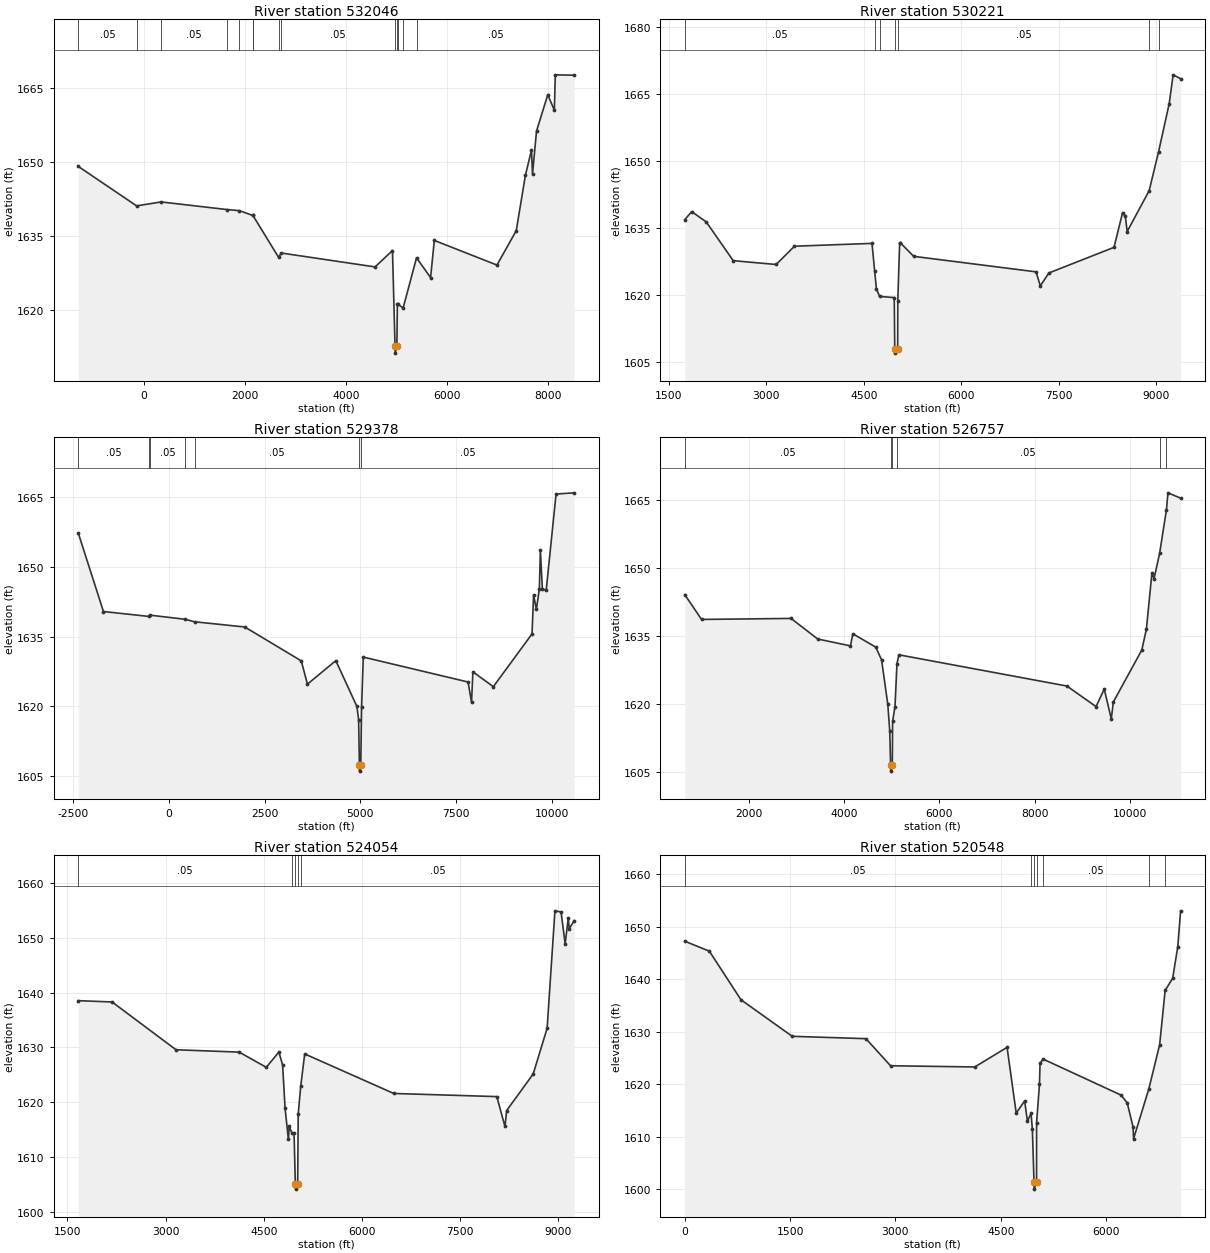
Type RM Length L Ch R = 1,532046,1825,1825,1825
BEGIN DESCRIPTION:
Mapping XS ef78b45c
END DESCRIPTION:
XS GIS Cut Line= 4
      1562099.07      6910454.20      1564369.92      6905516.68
      1565078.25      6903995.85      1565369.92      6901308.31
#Sta/Elev= 30
 -1294.3 1649.03  -140.0 1641.04   345.1 1641.84  1654.8 1640.29  1891.5 1640.08
  2154.2 1639.12  2159.6 1639.14  2671.3 1630.60  2721.3 1631.49  4580.2 1628.67
  4924.9 1631.99  4975.4 1612.60  4978.4 1611.20  5011.4 1612.60  5021.9 1621.14
  5032.5 1621.09  5136.1 1620.36  5400.9 1630.52  5679.0 1626.51  5753.1 1634.04
  6992.8 1629.05  7375.0 1636.01  7556.1 1647.23  7676.8 1652.35  7696.9 1647.51
  7776.5 1656.19  7998.7 1663.57  8129.4 1660.43  8148.0 1667.60  8521.4 1667.52
#Mann=14,-1,0
 -1294.3    0.05       0  -140.0   0.075       0   345.1    0.05       0
  1654.8   0.075       0  1891.5    0.05       0  2154.2    0.12       0
  2159.6    0.05       0  2671.3    0.12       0  2721.3    0.05       0
  4975.4    0.05       0  5011.4    0.05       0  5032.5     0.1       0
  5136.1    0.12       0  5400.9    0.05       0
Bank Sta=4975.4,5011.4
Exp/Cntr=0.3,0.1

Type RM Length L Ch R = 1,530221,843,843,843
BEGIN DESCRIPTION:
Mapping XS 8a25470f
END DESCRIPTION:
XS GIS Cut Line= 5
      1565040.45      6907127.53      1565630.73      6905512.94
      1566099.48      6903880.99      1566741.84      6901745.58
      1567019.62      6899783.72
#Sta/Elev= 30
  1747.4 1636.89  1853.4 1638.68  2077.0 1636.39  2492.2 1627.69  3152.3 1626.83
  3434.9 1630.93  4627.4 1631.56  4668.7 1625.33  4694.8 1621.42  4743.8 1619.67
  4969.9 1619.41  4977.5 1607.96  4981.3 1606.96  5022.5 1607.96  5024.3 1618.67
  5052.8 1631.54  5063.5 1631.69  5268.6 1628.66  7151.7 1625.18  7217.0 1622.03
  7349.1 1624.93  8351.4 1630.68  8482.7 1638.46  8525.3 1637.62  8553.4 1634.22
  8892.0 1643.39  9037.2 1652.15  9199.8 1662.86  9260.4 1669.35  9375.8 1668.48
#Mann=7,-1,0
  1747.4    0.05       0  4668.7    0.12       0  4743.8    0.05       0
  4977.5    0.05       0  5022.5    0.05       0  8892.0    0.12       0
  9037.2    0.05       0
Bank Sta=4977.5,5022.5
Exp/Cntr=0.3,0.1

Type RM Length L Ch R = 1,529378,2621,2621,2621
BEGIN DESCRIPTION:
Mapping XS f768a388
END DESCRIPTION:
XS GIS Cut Line= 5
      1563661.58      6911225.02      1565953.25      6905870.85
      1567001.40      6903810.36      1566911.58      6901641.68
      1567640.75      6899100.00
#Sta/Elev= 30
 -2363.2 1657.29 -1707.4 1640.43  -530.1 1639.38  -492.5 1639.65   427.7 1638.76
   673.0 1638.22  1984.6 1637.10  3459.6 1629.80  3621.1 1624.79  4362.5 1629.85
  4913.1 1619.98  4957.6 1617.17  4977.9 1607.46  4980.9 1606.06  5013.9 1607.46
  5034.7 1619.79  5079.6 1630.62  7816.7 1625.25  7906.7 1620.86  7942.4 1627.44
  8476.8 1624.25  9486.6 1635.61  9528.0 1644.03  9600.7 1640.87  9678.5 1645.38
  9705.1 1653.64  9757.1 1645.25  9857.6 1645.04 10114.6 1665.73 10587.3 1665.99
#Mann=7,-1,0
 -2363.2    0.05       0  -530.1   0.075       0  -492.5    0.05       0
   427.7   0.075       0   673.0    0.05       0  4977.9    0.03       0
  5013.9    0.05       0
Bank Sta=4977.9,5013.9
Exp/Cntr=0.3,0.1

Type RM Length L Ch R = 1,526757,2703,2703,2703
BEGIN DESCRIPTION:
Mapping XS 1039033d
END DESCRIPTION:
XS GIS Cut Line= 2
      1568932.42      6909537.51      1567953.25      6899183.31
#Sta/Elev= 30
   661.5 1644.06  1012.6 1638.60  2890.9 1638.82  3448.6 1634.28  4136.4 1632.76
  4186.7 1635.43  4668.8 1632.47  4789.3 1629.66  4919.9 1619.84  4960.1 1614.01
  4978.1 1606.52  4981.1 1605.12  5014.1 1606.52  5020.4 1616.10  5070.6 1619.38
  5111.9 1628.83  5152.1 1630.79  8676.6 1623.90  9287.5 1619.36  9460.1 1623.23
  9607.5 1616.65  9650.9 1620.39 10247.6 1631.85 10344.0 1636.46 10459.3 1648.78
 10504.7 1647.61 10621.0 1653.17 10765.0 1662.82 10796.0 1666.54 11061.9 1665.37
#Mann=6,-1,0
   661.5    0.05       0  4978.1    0.05       0  5014.1    0.05       0
  5111.9    0.05       0 10621.0    0.12       0 10765.0    0.05       0
Bank Sta=4978.1,5014.1
Exp/Cntr=0.3,0.1

Type RM Length L Ch R = 1,524054,3506,3506,3506
BEGIN DESCRIPTION:
Mapping XS d247e3b4
END DESCRIPTION:
XS GIS Cut Line= 3
      1570821.70      6906641.41      1569866.84      6904245.58
      1568234.88      6899523.32
#Sta/Elev= 30
  1666.8 1638.53  2183.2 1638.29  3159.2 1629.58  4124.4 1629.15  4538.3 1626.38
  4730.7 1629.16  4787.8 1626.80  4825.3 1618.97  4876.0 1613.25  4888.7 1615.59
  4933.3 1614.32  4962.8 1614.36  4982.0 1605.17  4985.0 1604.17  5018.0 1605.17
  5026.3 1617.86  5064.2 1622.90  5125.4 1628.82  6486.4 1621.61  8060.3 1621.04
  8185.1 1615.59  8210.9 1618.50  8616.3 1625.16  8829.2 1633.50  8948.6 1654.91
  9042.2 1654.70  9104.5 1648.90  9152.6 1653.66  9166.9 1651.64  9242.2 1653.12
#Mann=5,-1,0
  1666.8    0.05       0  4933.3     0.1       0  4982.0    0.07       0
  5018.0     0.1       0  5064.2    0.05       0
Bank Sta=4982,5018
Exp/Cntr=0.3,0.1

Type RM Length L Ch R = 1,520548,3893,3893,3893
BEGIN DESCRIPTION:
Clear Fork Brazos Rv 128.0
END DESCRIPTION:
XS GIS Cut Line= 3
      1571805.00      6907188.04      1571805.00      6902188.00
      1571305.00      6900187.99
#Sta/Elev= 30
     0.5 1647.23   350.5 1645.33   800.5 1636.09  1530.5 1629.14  2580.5 1628.69
  2930.5 1623.54  4130.5 1623.31  4590.5 1627.04  4720.5 1614.54  4840.5 1616.84
  4880.5 1613.00  4931.8 1614.48  4950.5 1611.50  4974.2 1601.47  4977.2 1600.07
  5010.2 1601.47  5010.8 1612.71  5052.1 1620.05  5059.8 1623.99  5103.2 1624.81
  6214.3 1617.95  6301.9 1616.47  6384.4 1611.89  6392.1 1609.66  6609.1 1619.13
  6763.2 1627.52  6841.4 1637.86  6948.7 1640.18  7020.9 1646.14  7062.1 1653.01
#Mann=7,-1,0
     0.5    0.05       0  4931.8    0.12       0  4974.2    0.07       0
  5010.2    0.12       0  5103.2    0.05       0  6609.1    0.12       0
  6841.4    0.05       0
Bank Sta=4974.2,5010.2
Exp/Cntr=0.3,0.1

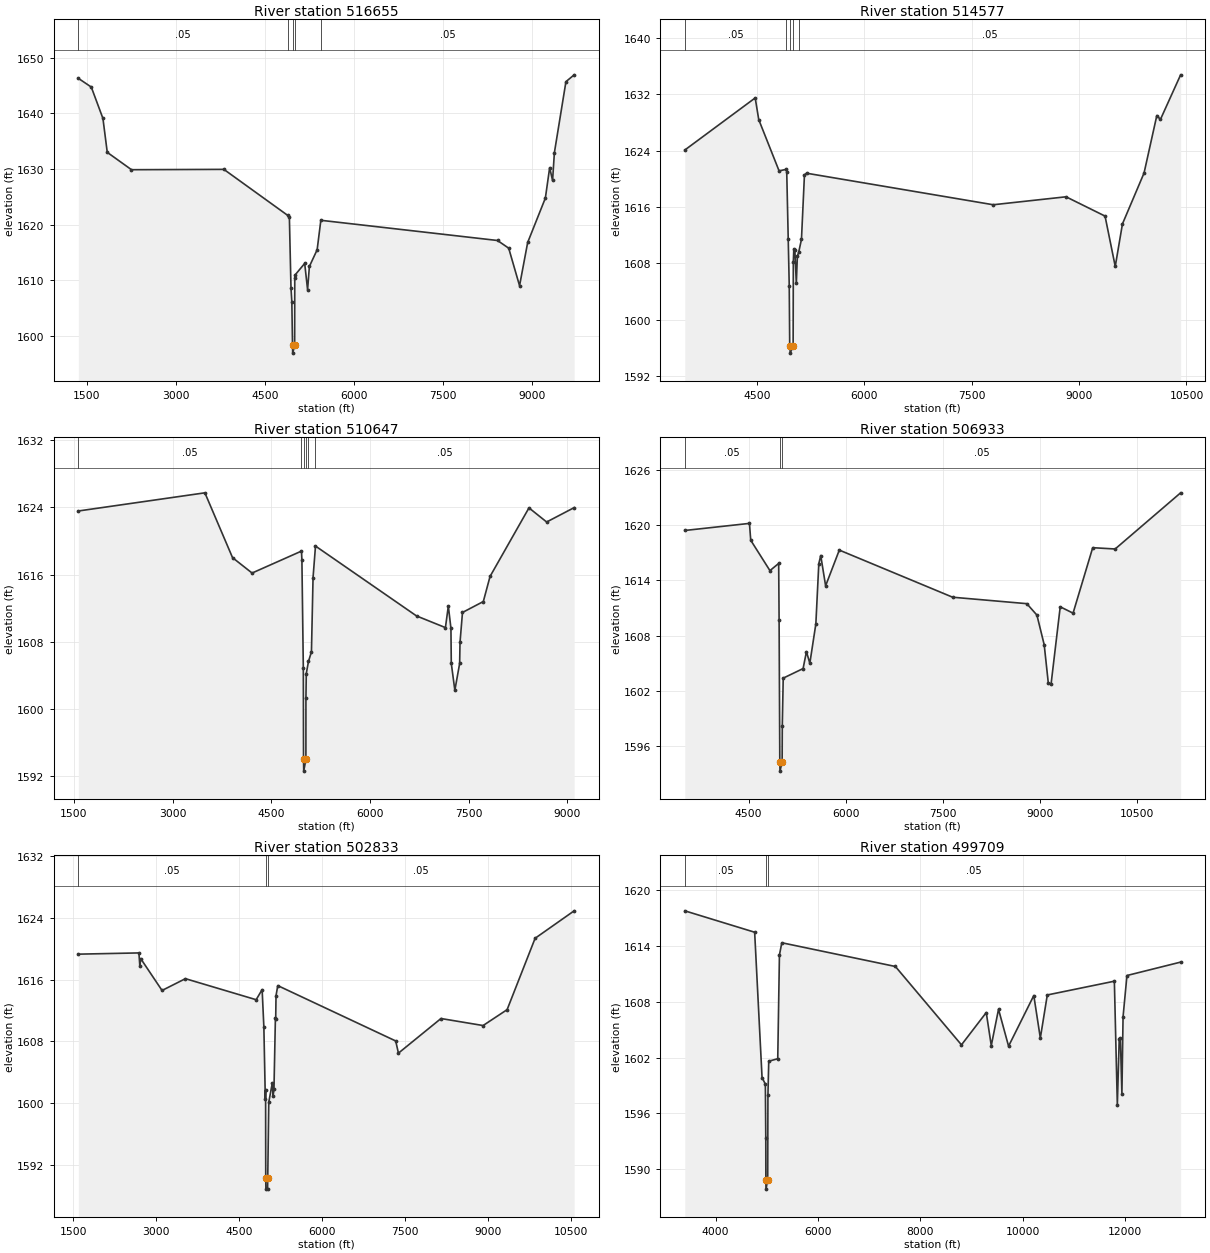
Type RM Length L Ch R = 1,516655,2078,2078,2078
BEGIN DESCRIPTION:
Clear Fork Brazos Rv 127.0
END DESCRIPTION:
XS GIS Cut Line= 3
      1573704.99      6907288.04      1574705.00      6903788.00
      1572204.99      6899787.99
#Sta/Elev= 30
  1358.7 1646.28  1577.1 1644.71  1773.4 1639.07  1846.2 1632.98  2254.5 1629.86
  3811.9 1629.92  4885.4 1621.67  4915.6 1621.41  4942.9 1608.66  4957.2 1606.13
  4968.8 1598.30  4971.8 1596.90  5004.8 1598.30  5006.5 1610.45  5012.4 1610.95
  5173.9 1613.02  5222.8 1608.29  5252.9 1612.47  5383.8 1615.47  5446.2 1620.77
  8423.9 1617.14  8612.6 1615.76  8795.4 1609.01  8932.2 1616.78  9230.5 1624.76
  9303.0 1630.23  9352.0 1627.93  9382.6 1632.92  9577.2 1645.68  9715.8 1646.91
#Mann=5,-1,0
  1358.7    0.05       0  4885.4    0.12       0  4968.8    0.07       0
  5004.8    0.12       0  5446.2    0.05       0
Bank Sta=4968.8,5004.8
Exp/Cntr=0.3,0.1

Type RM Length L Ch R = 1,514577,3930,3930,3930
BEGIN DESCRIPTION:
Mapping XS 15226ee3
END DESCRIPTION:
XS GIS Cut Line= 3
      1577227.97      6904488.65      1576099.48      6903117.11
      1573095.98      6898933.04
#Sta/Elev= 30
  3491.6 1624.07  4475.1 1631.47  4524.6 1628.39  4808.7 1621.11  4905.5 1621.32
  4915.5 1621.02  4936.4 1611.46  4950.7 1604.76  4957.2 1596.33  4960.0 1596.23
  4963.8 1595.23  5005.0 1596.23  5007.6 1608.18  5014.6 1610.05  5028.9 1609.87
  5049.7 1605.16  5064.1 1609.01  5082.3 1609.53  5121.4 1611.38  5163.1 1620.54
  5191.8 1620.78  7800.5 1616.30  8817.3 1617.43  9362.4 1614.69  9504.9 1607.54
  9605.6 1613.58  9907.4 1620.81 10085.7 1628.97 10136.0 1628.41 10418.2 1634.75
#Mann=5,-1,0
  3491.6    0.05       0  4905.5     0.1       0  4960.0    0.07       0
  5005.0     0.1       0  5082.3    0.05       0
Bank Sta=4960,5005
Exp/Cntr=0.3,0.1

Type RM Length L Ch R = 1,510647,3714,3714,3714
BEGIN DESCRIPTION:
Mapping XS 48af7542
END DESCRIPTION:
XS GIS Cut Line= 3
      1578557.40      6904641.64      1577619.92      6901850.01
      1575932.40      6897579.15
#Sta/Elev= 30
  1566.3 1623.57  3490.0 1625.73  3910.4 1618.02  4207.3 1616.19  4958.6 1618.80
  4964.9 1617.71  4986.4 1604.86  4989.5 1594.03  4992.5 1592.63  5025.5 1594.03
  5026.0 1601.29  5031.4 1604.24  5065.0 1605.68  5109.8 1606.82  5134.2 1615.65
  5171.4 1619.40  6706.8 1611.09  7146.4 1609.70  7190.6 1612.26  7230.2 1609.63
  7235.6 1605.45  7289.7 1602.24  7362.7 1605.44  7368.1 1607.93  7405.7 1611.50
  7722.4 1612.80  7825.0 1615.79  8416.4 1623.94  8685.2 1622.26  9103.3 1623.97
#Mann=6,-1,0
  1566.3    0.05       0  4958.6     0.1       0  4989.5    0.07       0
  5025.5     0.1       0  5065.0    0.12       0  5171.4    0.05       0
Bank Sta=4989.5,5025.5
Exp/Cntr=0.3,0.1

Type RM Length L Ch R = 1,506933,4100,4100,4100
BEGIN DESCRIPTION:
Mapping XS afa7b18e
END DESCRIPTION:
XS GIS Cut Line= 5
      1581255.72      6902960.83      1580960.59      6901693.49
      1580769.62      6901467.80      1579589.06      6900946.97
      1576342.54      6897440.03
#Sta/Elev= 30
  3513.1 1619.41  4512.7 1620.18  4532.5 1618.35  4829.4 1615.05  4964.6 1615.83
  4971.1 1609.74  4982.0 1594.27  4985.0 1593.27  5018.0 1594.27  5020.5 1598.17
  5034.8 1603.37  5342.0 1604.41  5394.1 1606.25  5446.2 1604.98  5539.4 1609.26
  5585.0 1615.80  5614.9 1616.69  5690.3 1613.40  5902.0 1617.28  7654.8 1612.16
  8801.2 1611.46  8957.2 1610.22  9070.0 1607.00  9134.0 1602.80  9176.6 1602.75
  9317.8 1611.12  9516.2 1610.43  9820.1 1617.54 10167.1 1617.40 11179.3 1623.50
#Mann=3,-1,0
  3513.1    0.05       0  4982.0    0.05       0  5018.0    0.05       0
Bank Sta=4982,5018
Exp/Cntr=0.3,0.1

Type RM Length L Ch R = 1,502833,3124,3124,3124
BEGIN DESCRIPTION:
Mapping XS 7ae39abf
END DESCRIPTION:
XS GIS Cut Line= 3
      1581554.27      6903010.24      1580165.37      6898947.73
      1576502.17      6896048.42
#Sta/Elev= 30
  1592.6 1619.30  2688.2 1619.46  2704.6 1617.76  2719.6 1618.73  3106.2 1614.59
  3529.0 1616.12  4807.7 1613.39  4916.0 1614.70  4947.3 1609.85  4973.4 1600.56
  4978.7 1601.65  4981.2 1590.22  4984.2 1588.82  5014.2 1588.82  5017.2 1590.22
  5036.0 1600.10  5098.6 1602.54  5114.2 1600.92  5129.9 1601.77  5155.9 1611.02
  5161.2 1610.83  5167.0 1613.91  5198.7 1615.22  7330.8 1608.04  7380.5 1606.46
  8149.8 1610.95  8911.0 1610.04  9345.4 1612.10  9851.9 1621.36 10557.7 1624.92
#Mann=3,-1,0
  1592.6    0.05       0  4981.2    0.05       0  5017.2    0.05       0
Bank Sta=4981.2,5017.2
Exp/Cntr=0.3,0.1

Type RM Length L Ch R = 1,499709,3999,3999,3999
BEGIN DESCRIPTION:
Mapping XS ec7414e6
END DESCRIPTION:
XS GIS Cut Line= 5
      1582280.04      6902874.08      1581724.48      6901016.41
      1581672.40      6900009.47      1580127.26      6894974.74
      1578808.91      6894315.57
#Sta/Elev= 30
  3398.3 1617.77  4763.2 1615.47  4907.7 1599.86  4972.3 1599.15  4980.7 1593.31
  4982.0 1588.87  4985.0 1587.87  5018.0 1588.87  5022.5 1597.95  5038.5 1601.61
  5214.4 1601.88  5247.5 1613.03  5293.9 1614.34  7513.0 1611.79  8803.9 1603.37
  9288.3 1606.84  9386.5 1603.29  9527.9 1607.19  9724.3 1603.23 10217.4 1608.67
 10344.9 1604.10 10481.0 1608.73 11791.3 1610.21 11849.4 1596.93 11886.4 1604.03
 11908.7 1604.13 11938.8 1598.11 11961.2 1606.38 12037.3 1610.82 13086.0 1612.26
#Mann=3,-1,0
  3398.3    0.05       0  4982.0    0.05       0  5018.0    0.05       0
Bank Sta=4982,5018
Exp/Cntr=0.3,0.1

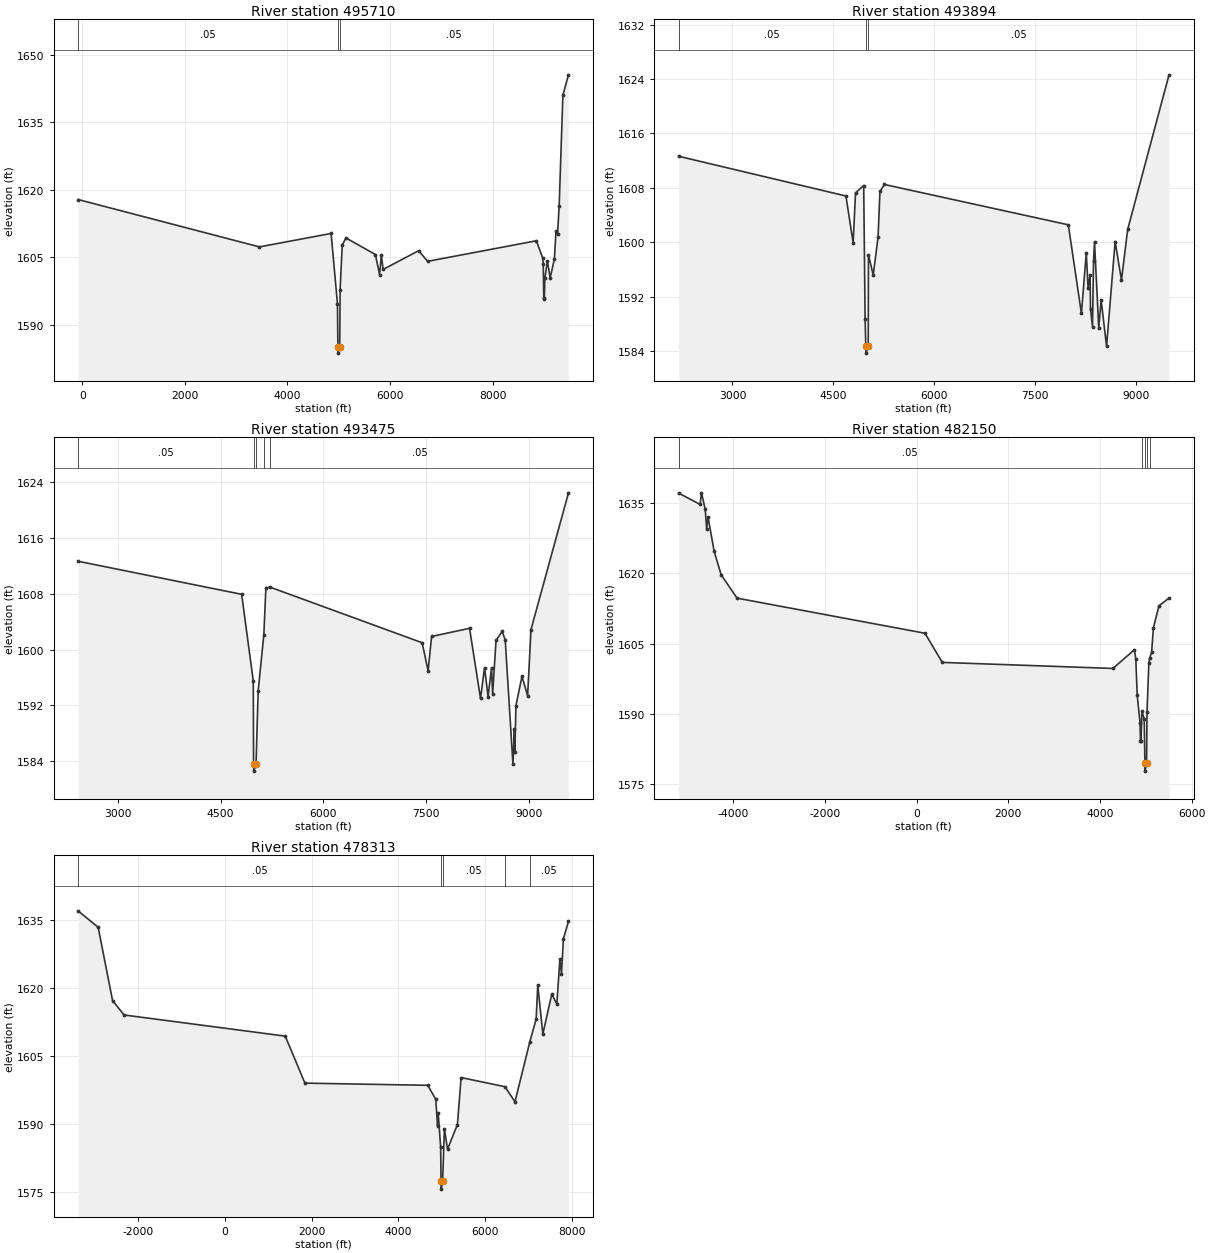
Type RM Length L Ch R = 1,495710,1816,1816,1816
BEGIN DESCRIPTION:
Mapping XS 32d1820f
END DESCRIPTION:
XS GIS Cut Line= 4
      1582883.81      6903468.06      1583238.29      6902333.15
      1583161.58      6899391.68      1581786.77      6894142.38
#Sta/Elev= 30
   -80.6 1617.85  3454.3 1607.33  4851.1 1610.32  4974.7 1594.70  4983.0 1585.15
  4986.0 1583.75  5019.0 1585.15  5026.4 1597.84  5067.7 1607.72  5140.1 1609.32
  5714.3 1605.64  5795.1 1601.20  5830.4 1605.56  5863.7 1602.32  6556.3 1606.49
  6732.0 1604.13  8851.2 1608.69  8975.2 1604.87  8985.5 1603.54  8995.9 1595.89
  9006.2 1595.72  9016.6 1600.37  9066.4 1604.24  9119.9 1600.43  9202.6 1604.68
  9233.6 1610.79  9263.3 1610.15  9295.7 1616.44  9368.0 1641.02  9477.2 1645.53
#Mann=3,-1,0
   -80.6    0.05       0  4983.0    0.05       0  5019.0    0.05       0
Bank Sta=4983,5019
Exp/Cntr=0.3,0.1

Type RM Length L Ch R = 1,493894,419,419,419
BEGIN DESCRIPTION:
Mapping XS 1bf80fd8
END DESCRIPTION:
XS GIS Cut Line= 6
      1583407.12      6901860.01      1583900.36      6899687.06
      1584780.21      6898833.87      1586206.63      6897020.85
      1586593.23      6896460.95      1586766.54      6895647.75
#Sta/Elev= 30
  2199.9 1612.64  4686.7 1606.80  4794.1 1599.92  4829.3 1607.27  4950.8 1608.34
  4971.9 1588.65  4982.0 1584.70  4985.0 1583.70  5018.0 1584.70  5021.5 1598.17
  5092.0 1595.18  5164.1 1600.73  5192.3 1607.46  5258.6 1608.49  7991.9 1602.56
  8186.4 1589.53  8258.5 1598.45  8285.6 1593.34  8315.3 1595.18  8321.4 1590.21
  8351.1 1587.61  8366.0 1597.20  8380.8 1600.07  8443.8 1587.42  8479.6 1591.52
  8560.0 1584.70  8687.3 1600.10  8781.2 1594.43  8874.5 1601.91  9488.2 1624.61
#Mann=3,-1,0
  2199.9    0.05       0  4982.0    0.03       0  5018.0    0.05       0
Bank Sta=4982,5018
Exp/Cntr=0.3,0.1

Type RM Length L Ch R = 1,493475,11325,11325,11325
BEGIN DESCRIPTION:
Mapping XS d45f5f49
END DESCRIPTION:
XS GIS Cut Line= 6
      1583647.07      6901886.69      1584273.63      6899780.38
      1584980.18      6899153.82      1586193.30      6897340.80
      1586953.17      6895981.03      1586926.51      6895714.41
#Sta/Elev= 30
  2423.6 1612.69  4808.2 1607.94  4978.0 1595.49  4982.0 1583.56  4985.0 1582.56
  5018.0 1583.56  5049.1 1594.07  5131.5 1602.11  5162.0 1608.88  5225.3 1608.96
  7439.4 1600.99  7526.4 1596.96  7577.5 1601.89  8130.6 1603.06  8290.5 1592.99
  8349.1 1597.41  8400.6 1593.27  8451.0 1597.40  8467.3 1593.64  8516.8 1601.32
  8605.4 1602.62  8650.7 1601.41  8763.2 1583.56  8785.1 1588.63  8790.8 1585.35
  8807.0 1591.95  8894.8 1596.17  8976.9 1593.40  9026.5 1602.89  9572.9 1622.51
#Mann=5,-1,0
  2423.6    0.05       0  4982.0    0.05       0  5018.0    0.05       0
  5131.5    0.12       0  5225.3    0.05       0
Bank Sta=4982,5018
Exp/Cntr=0.3,0.1

Type RM Length L Ch R = 1,482150,3837,3837,3837
BEGIN DESCRIPTION:
Clear Fork Brazos Rv 123.0
END DESCRIPTION:
XS GIS Cut Line= 3
      1587004.99      6907038.04      1589005.00      6897038.00
      1589005.00      6896537.98
#Sta/Elev= 30
 -5192.1 1637.13 -4722.9 1634.72 -4692.4 1637.19 -4610.8 1633.65 -4580.2 1629.46
 -4549.6 1632.03 -4417.0 1624.75 -4264.0 1619.71 -3917.3 1614.72   182.3 1607.23
   559.6 1601.01  4281.9 1599.72  4751.0 1603.71  4781.6 1601.75  4812.2 1594.01
  4873.4 1588.17  4883.6 1584.34  4893.8 1584.21  4914.6 1590.58  4965.2 1588.97
  4980.2 1579.51  4983.2 1577.81  5016.2 1579.51  5026.0 1590.38  5066.0 1600.81
  5082.1 1601.89  5126.0 1603.16  5166.0 1608.40  5286.0 1613.07  5506.0 1614.74
#Mann=5,-1,0
 -5192.1    0.05       0  4914.6     0.1       0  4980.2    0.07       0
  5016.2     0.1       0  5082.1    0.05       0
Bank Sta=4980.2,5016.2
Exp/Cntr=0.3,0.1

Type RM Length L Ch R = 1,478313,3829,3829,3829
BEGIN DESCRIPTION:
Clear Fork Brazos Rv 122.0
END DESCRIPTION:
XS GIS Cut Line= 4
      1587439.68      6906742.88      1588355.00      6901988.00
      1590855.00      6899488.00      1593355.01      6897987.99
#Sta/Elev= 30
 -3378.3 1637.08 -2915.1 1633.44 -2583.6 1617.27 -2318.9 1614.10  1392.6 1609.43
  1845.7 1599.06  4674.1 1598.58  4858.0 1595.51  4900.4 1589.57  4914.6 1592.45
  4971.1 1584.96  4980.4 1577.37  4983.4 1575.67  5016.4 1577.37  5057.7 1589.00
  5129.6 1584.46  5357.0 1589.91  5442.6 1600.29  6452.7 1598.27  6682.6 1594.94
  7022.5 1608.10  7170.5 1613.21  7207.4 1620.73  7324.0 1609.90  7530.0 1618.68
  7646.7 1616.51  7716.6 1626.38  7753.6 1623.22  7798.3 1630.96  7914.9 1634.76
#Mann=5,-1,0
 -3378.3    0.05       0  4980.4    0.05       0  5016.4    0.05       0
  6452.7    0.12       0  7022.5    0.05       0
Bank Sta=4980.4,5016.4
Exp/Cntr=0.3,0.1