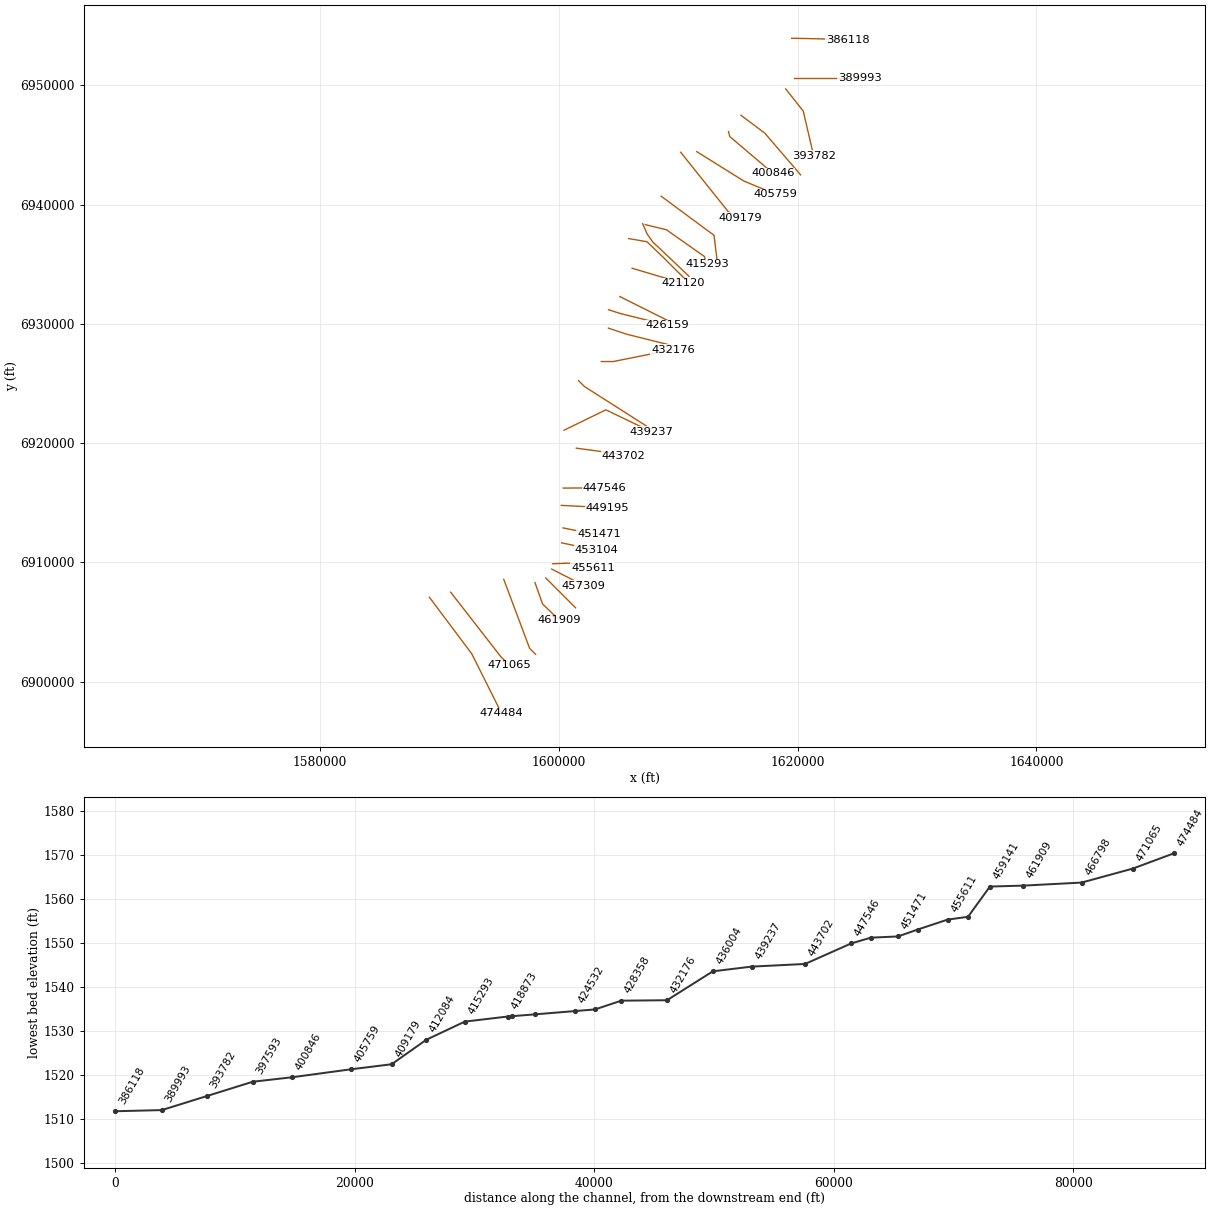
HEC-RAS study Clear Fork Brazos Rv.prj: Clear Fork Brazos Rv Base Level Engineering

--- Clear Fork Brazos Rv.g01 (geometry) --- (continued)

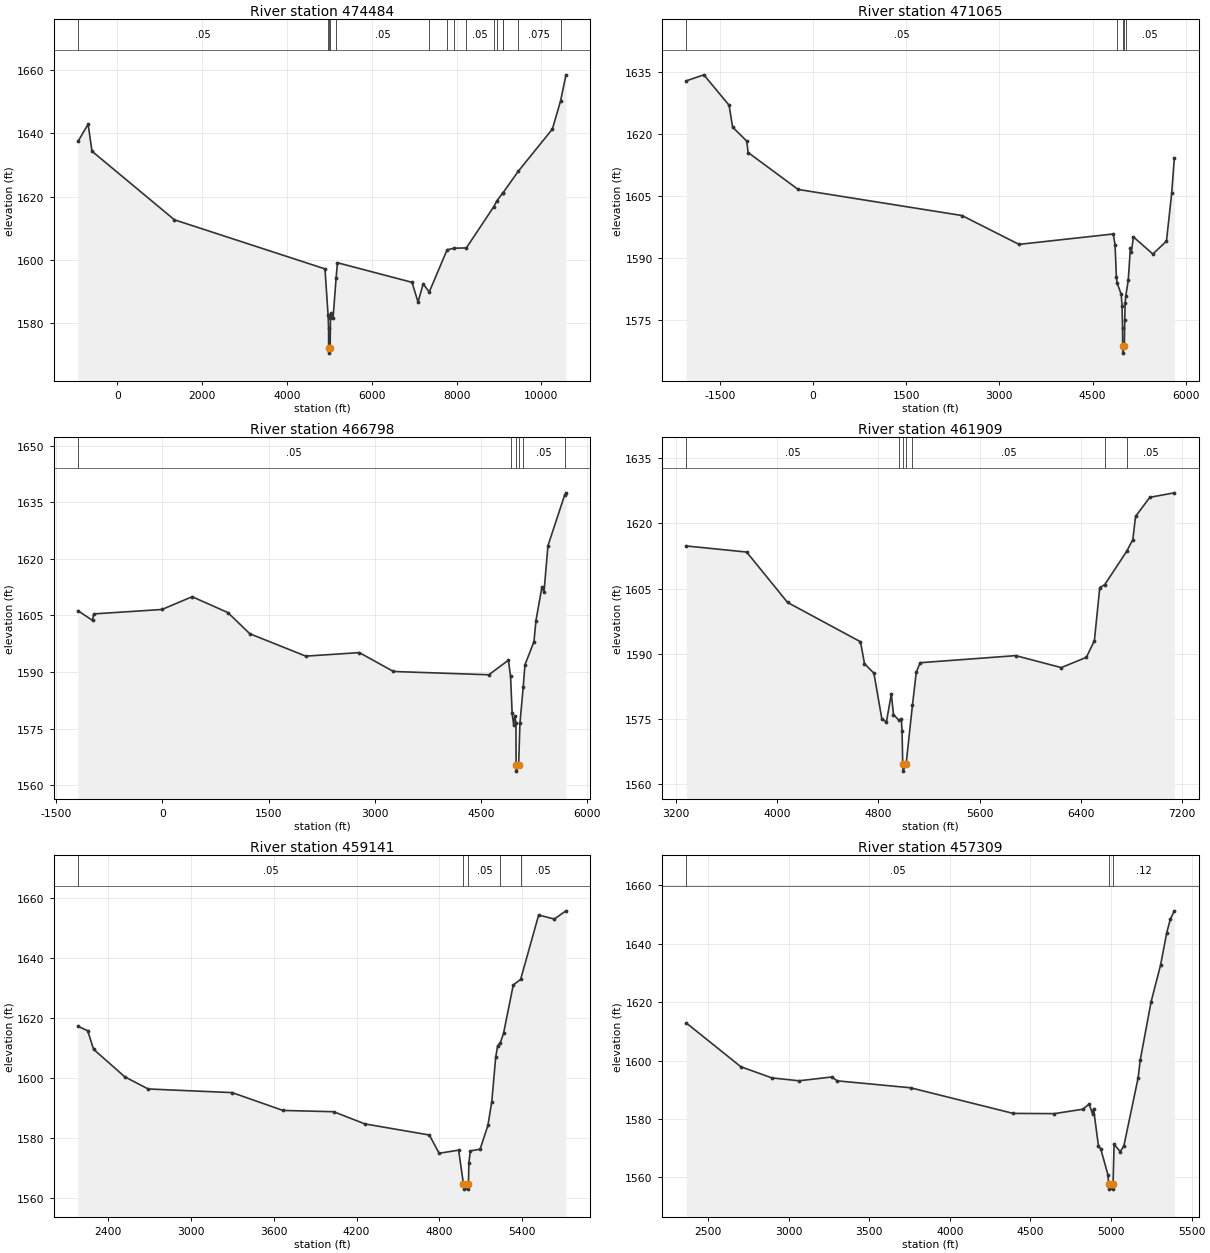
Type RM Length L Ch R = 1,474484,3419,3419,3419
BEGIN DESCRIPTION:
Clear Fork Brazos Rv 121.0
END DESCRIPTION:
XS GIS Cut Line= 4
      1589154.30      6907072.27      1591205.00      6904338.00
      1592705.00      6902338.00      1595205.00      6897338.00
#Sta/Elev= 30
  -927.4 1637.45  -687.7 1642.92  -596.0 1634.37  1347.7 1612.63  4897.7 1597.07
  4970.6 1582.48  4983.1 1578.19  4983.8 1572.07  4986.8 1570.37  5019.8 1572.07
  5026.8 1581.41  5035.2 1583.00  5088.3 1581.40  5159.6 1594.14  5191.7 1599.02
  6949.8 1592.81  7092.3 1586.54  7212.5 1592.31  7356.6 1589.76  7777.7 1603.13
  7946.7 1603.63  8231.3 1603.72  8879.2 1616.81  8950.3 1618.61  9091.4 1621.18
  9093.9 1621.14  9451.8 1627.95 10259.2 1641.38 10452.9 1650.30 10580.6 1658.58
#Mann=15,-1,0
  -927.4    0.05       0  4970.6     0.1       0  4983.8    0.07       0
  5019.8     0.1       0  5159.6    0.05       0  7356.6    0.12       0
  7777.7    0.05       0  7946.7    0.12       0  8231.3    0.05       0
  8879.2    0.12       0  8950.3    0.05       0  9091.4    0.12       0
  9093.9    0.05       0  9451.8   0.075       0 10452.9     0.1       0
Bank Sta=4983.8,5019.8
Exp/Cntr=0.3,0.1

Type RM Length L Ch R = 1,471065,4267,4267,4267
BEGIN DESCRIPTION:
Clear Fork Brazos Rv 120.0
END DESCRIPTION:
XS GIS Cut Line= 4
      1590934.65      6907503.61      1593355.00      6904388.00
      1595144.80      6902084.07      1595854.97      6901388.03
#Sta/Elev= 30
 -2039.6 1632.90 -1757.0 1634.35 -1350.7 1626.98 -1294.5 1621.69 -1066.5 1618.29
 -1044.8 1615.53  -239.3 1606.58  2398.0 1600.26  3316.6 1593.27  4834.7 1595.79
  4862.9 1593.15  4884.1 1585.40  4896.1 1583.91  4962.0 1581.19  4976.1 1578.24
  4983.1 1572.98  4985.7 1568.62  4987.9 1566.92  5012.7 1568.62  5018.5 1574.92
  5025.5 1578.96  5035.1 1580.71  5075.1 1584.56  5110.4 1592.44  5124.5 1591.50
  5159.8 1595.07  5471.0 1590.93  5690.3 1594.05  5775.2 1605.72  5817.5 1614.24
#Mann=5,-1,0
 -2039.6    0.05       0  4896.1     0.1       0  4985.7    0.07       0
  5012.7     0.1       0  5035.1    0.05       0
Bank Sta=4985.7,5012.7
Exp/Cntr=0.3,0.1

Type RM Length L Ch R = 1,466798,4889,4889,4889
BEGIN DESCRIPTION:
Clear Fork Brazos Rv 119.0
END DESCRIPTION:
XS GIS Cut Line= 4
      1595382.54      6908581.23      1596055.00      6906788.00
      1597555.00      6902788.00      1598055.01      6902287.99
#Sta/Elev= 30
 -1192.4 1606.27  -986.0 1603.69  -970.9 1605.42    -6.1 1606.59   421.1 1609.98
   925.7 1605.77  1235.4 1600.16  2025.7 1594.23  2783.1 1595.16  3264.6 1590.16
  4613.0 1589.29  4888.0 1593.15  4918.8 1588.94  4941.4 1579.04  4962.7 1576.03
  4979.6 1578.45  4994.8 1576.45  4997.2 1565.45  5000.2 1563.75  5033.2 1565.45
  5051.3 1576.40  5098.3 1586.15  5122.1 1591.92  5249.3 1598.04  5277.6 1603.63
  5362.5 1612.62  5390.8 1611.14  5447.3 1623.50  5682.6 1636.89  5701.9 1637.51
#Mann=6,-1,0
 -1192.4    0.05       0  4918.8     0.1       0  4997.2    0.07       0
  5033.2     0.1       0  5098.3    0.05       0  5682.6    0.12       0
Bank Sta=4997.2,5033.2
Exp/Cntr=0.3,0.1

Type RM Length L Ch R = 1,461909,2768,2768,2768
BEGIN DESCRIPTION:
Mapping XS 067c21bc
END DESCRIPTION:
XS GIS Cut Line= 3
      1598001.41      6908305.78      1598639.45      6906508.87
      1600045.71      6905154.69
#Sta/Elev= 30
  3280.8 1614.80  3758.0 1613.40  4081.6 1601.82  4658.0 1592.79  4689.8 1587.75
  4764.1 1585.57  4826.5 1575.15  4862.7 1574.30  4902.0 1580.78  4919.1 1576.07
  4962.3 1574.73  4980.8 1575.13  4986.9 1572.18  4992.1 1564.76  4994.4 1563.06
  5019.1 1564.76  5068.9 1578.18  5099.0 1585.73  5129.8 1587.97  5885.3 1589.60
  6246.0 1586.85  6444.1 1589.21  6507.6 1593.02  6550.1 1605.24  6588.7 1605.89
  6762.4 1613.54  6811.7 1616.27  6833.1 1621.58  6946.0 1625.98  7139.9 1627.01
#Mann=7,-1,0
  3280.8    0.05       0  4962.3    0.12       0  4992.1    0.07       0
  5019.1    0.12       0  5068.9    0.05       0  6588.7    0.12       0
  6762.4    0.05       0
Bank Sta=4992.1,5019.1
Exp/Cntr=0.3,0.1

Type RM Length L Ch R = 1,459141,1832,1832,1832
BEGIN DESCRIPTION:
Clear Fork Brazos Rv 117.0
END DESCRIPTION:
XS GIS Cut Line= 3
      1598905.02      6908687.98      1600905.00      6906688.00
      1601404.99      6906188.01
#Sta/Elev= 30
  2181.9 1617.21  2252.6 1615.73  2295.0 1609.54  2521.3 1600.34  2691.0 1596.28
  3299.1 1595.07  3666.8 1589.12  4034.5 1588.69  4260.8 1584.62  4727.5 1580.92
  4798.2 1574.82  4939.6 1575.86  4974.8 1564.55  4977.8 1562.85  5007.8 1562.85
  5010.8 1564.55  5013.8 1571.53  5024.4 1575.61  5095.2 1576.18  5151.7 1584.10
  5180.0 1592.09  5208.3 1606.91  5222.4 1610.71  5241.2 1611.61  5264.9 1614.84
  5335.6 1631.02  5388.6 1632.83  5519.4 1654.35  5632.6 1653.01  5717.4 1655.75
#Mann=5,-1,0
  2181.9    0.05       0  4974.8    0.05       0  5010.8    0.05       0
  5241.2    0.12       0  5388.6    0.05       0
Bank Sta=4974.8,5010.8
Exp/Cntr=0.3,0.1

Type RM Length L Ch R = 1,457309,1698,1698,1698
BEGIN DESCRIPTION:
Mapping XS a1185eac
END DESCRIPTION:
XS GIS Cut Line= 2
      1599403.68      6909440.34      1602093.18      6908052.21
#Sta/Elev= 30
  2366.1 1612.87  2704.4 1597.89  2896.5 1594.07  3065.3 1593.08  3267.9 1594.38
  3302.5 1593.06  3756.6 1590.69  4393.4 1581.91  4648.0 1581.83  4825.3 1583.34
  4864.0 1585.10  4886.1 1581.67  4891.7 1583.44  4922.1 1570.74  4936.0 1569.81
  4980.4 1560.98  4985.6 1557.68  4987.8 1555.98  5010.3 1555.98  5012.6 1557.68
  5019.0 1571.31  5057.2 1568.82  5079.7 1570.80  5168.5 1594.20  5180.9 1600.11
  5248.5 1620.13  5307.1 1632.66  5345.7 1643.83  5367.9 1648.45  5392.7 1651.28
#Mann=3,-1,0
  2366.1    0.05       0  4985.6    0.07       0  5012.6    0.12       0
Bank Sta=4985.6,5012.6
Exp/Cntr=0.3,0.1

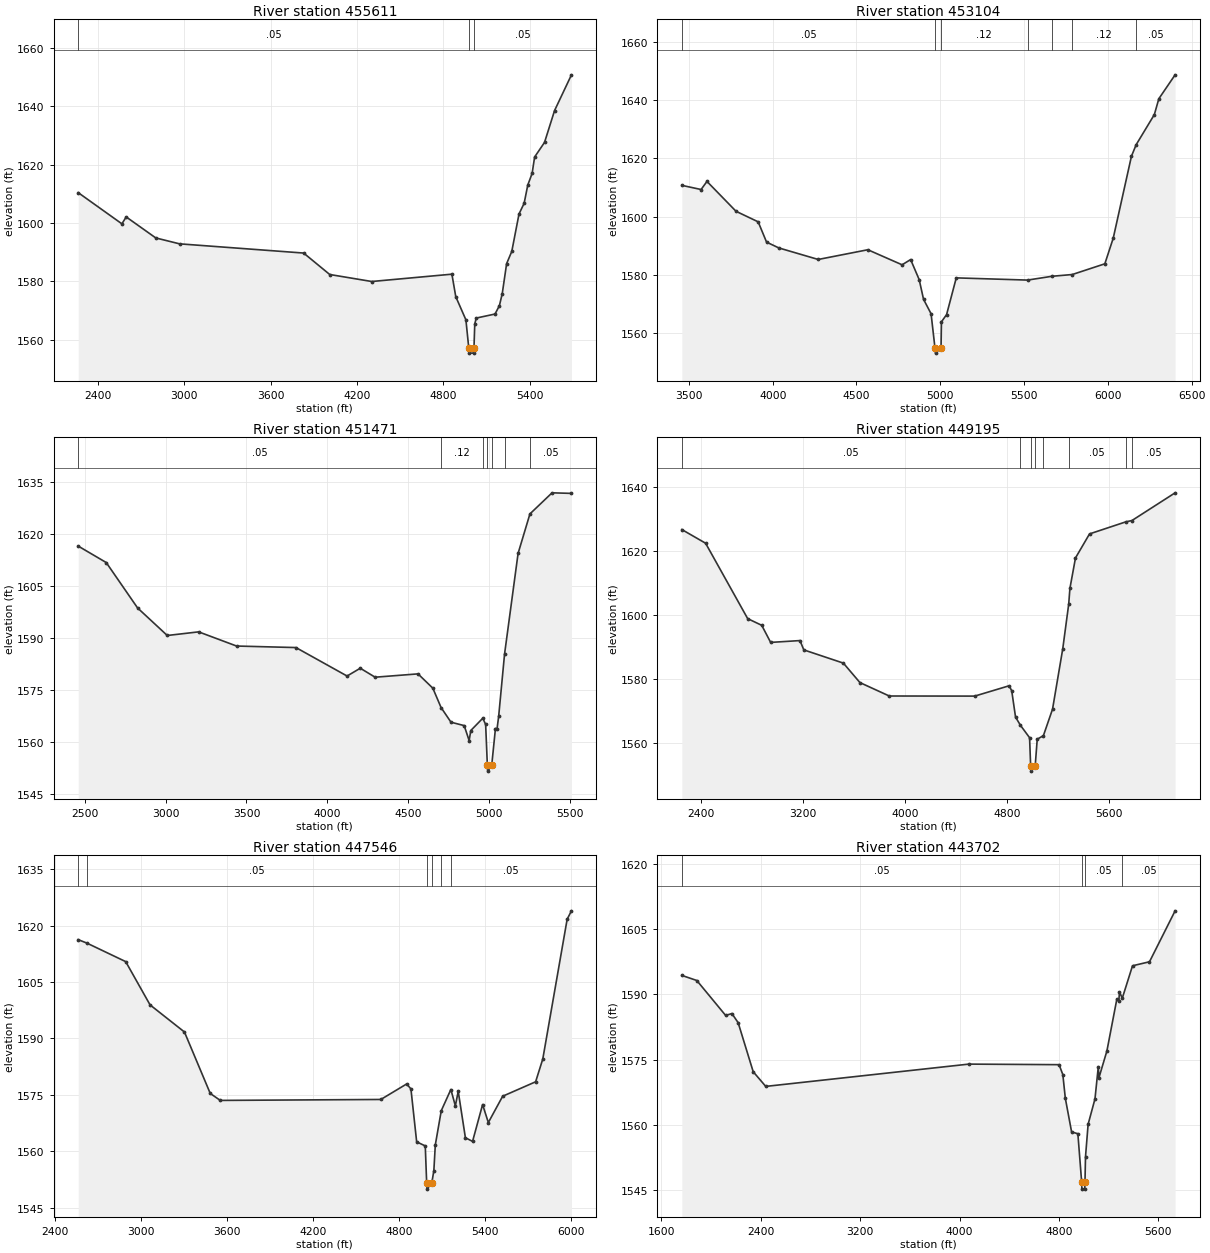
Type RM Length L Ch R = 1,455611,2507,2507,2507
BEGIN DESCRIPTION:
Clear Fork Brazos Rv 116.0
END DESCRIPTION:
XS GIS Cut Line= 4
      1599481.83      6909881.94      1600806.43      6909933.72
      1602206.96      6909777.31      1602855.03      6909537.99
#Sta/Elev= 30
  2264.2 1610.36  2567.6 1599.67  2597.6 1602.03  2803.1 1594.83  2967.9 1592.81
  3829.9 1589.65  4011.0 1582.30  4302.8 1579.90  4859.5 1582.41  4886.4 1574.70
  4956.8 1566.76  4976.8 1557.05  4979.8 1555.35  5009.8 1555.35  5012.8 1557.05
  5018.3 1565.37  5028.9 1567.37  5159.0 1568.75  5189.4 1571.62  5209.2 1575.75
  5239.6 1586.03  5275.4 1590.22  5325.6 1603.04  5361.3 1606.72  5386.4 1612.94
  5416.8 1616.97  5434.0 1622.57  5502.8 1627.58  5572.6 1638.50  5689.9 1650.74
#Mann=3,-1,0
  2264.2    0.05       0  4976.8    0.05       0  5012.8    0.05       0
Bank Sta=4976.8,5012.8
Exp/Cntr=0.3,0.1

Type RM Length L Ch R = 1,453104,1633,1633,1633
BEGIN DESCRIPTION:
Mapping XS af367788
END DESCRIPTION:
XS GIS Cut Line= 2
      1600228.34      6911636.53      1603110.16      6911037.59
#Sta/Elev= 30
  3457.9 1610.70  3572.7 1609.27  3607.7 1612.05  3781.3 1601.79  3913.3 1598.17
  3963.4 1591.21  4036.7 1589.21  4271.6 1585.25  4567.8 1588.59  4772.1 1583.42
  4823.1 1585.22  4874.2 1578.32  4900.1 1571.57  4945.1 1566.61  4968.5 1554.79
  4971.5 1553.09  5004.5 1554.79  5007.0 1563.85  5037.6 1566.31  5095.4 1578.93
  5520.6 1578.17  5667.0 1579.48  5787.6 1580.08  5982.0 1583.76  6032.1 1592.57
  6140.7 1620.69  6169.0 1624.67  6277.5 1635.01  6304.1 1640.43  6401.3 1648.65
#Mann=7,-1,0
  3457.9    0.05       0  4968.5    0.07       0  5004.5    0.12       0
  5520.6    0.12       0  5667.0    0.05       0  5787.6    0.12       0
  6169.0    0.05       0
Bank Sta=4968.5,5004.5
Exp/Cntr=0.3,0.1

Type RM Length L Ch R = 1,451471,2276,2276,2276
BEGIN DESCRIPTION:
Clear Fork Brazos Rv 115.0
END DESCRIPTION:
XS GIS Cut Line= 3
      1600354.96      6912888.01      1602855.00      6912388.00
      1603355.04      6912388.00
#Sta/Elev= 30
  2459.7 1616.44  2633.1 1611.69  2826.9 1598.59  3010.4 1590.65  3204.2 1591.70
  3438.8 1587.61  3805.9 1587.17  4122.0 1578.96  4203.6 1581.21  4295.4 1578.62
  4560.5 1579.58  4652.3 1575.45  4703.0 1569.88  4764.5 1565.64  4846.1 1564.66
  4876.7 1560.34  4886.9 1563.24  4961.1 1566.79  4978.7 1564.99  4989.3 1553.23
  4991.5 1551.53  5016.3 1553.23  5039.3 1563.82  5049.3 1563.75  5059.3 1567.36
  5095.6 1585.28  5179.3 1614.33  5252.5 1625.72  5389.3 1631.80  5509.3 1631.64
#Mann=7,-1,0
  2459.7    0.05       0  4703.0    0.12       0  4961.1     0.1       0
  4989.3    0.07       0  5016.3     0.1       0  5095.6    0.12       0
  5252.5    0.05       0
Bank Sta=4989.3,5016.3
Exp/Cntr=0.3,0.1

Type RM Length L Ch R = 1,449195,1649,1649,1649
BEGIN DESCRIPTION:
Mapping XS 61113104
END DESCRIPTION:
XS GIS Cut Line= 2
      1600208.82      6914776.72      1604075.99      6914581.41
#Sta/Elev= 30
  2249.9 1626.69  2436.3 1622.42  2766.7 1598.87  2876.9 1596.79  2947.0 1591.45
  3177.3 1592.02  3207.3 1589.11  3517.9 1584.98  3647.9 1578.90  3878.2 1574.71
  4549.0 1574.68  4819.4 1577.91  4839.4 1576.34  4869.4 1568.13  4907.7 1565.57
  4979.6 1561.69  4987.8 1552.95  4990.8 1551.25  5023.8 1552.95  5039.6 1561.22
  5088.2 1562.34  5159.8 1570.60  5239.9 1589.43  5286.8 1603.42  5296.2 1608.32
  5340.0 1617.83  5450.2 1625.33  5735.3 1629.10  5783.2 1629.51  6122.0 1638.16
#Mann=8,-1,0
  2249.9    0.05       0  4907.7    0.12       0  4987.8    0.05       0
  5023.8    0.12       0  5088.2    0.12       0  5286.8    0.05       0
  5735.3    0.12       0  5783.2    0.05       0
Bank Sta=4987.8,5023.8
Exp/Cntr=0.3,0.1

Type RM Length L Ch R = 1,447546,3844,3844,3844
BEGIN DESCRIPTION:
Clear Fork Brazos Rv 114.0
END DESCRIPTION:
XS GIS Cut Line= 3
      1600363.75      6916228.42      1602805.00      6916238.00
      1603805.03      6916238.00
#Sta/Elev= 30
  2559.0 1616.24  2619.7 1615.32  2890.3 1610.40  3060.3 1598.90  3300.3 1591.69
  3480.3 1575.36  3550.3 1573.51  4670.3 1573.76  4850.3 1577.88  4880.3 1576.57
  4920.3 1562.50  4980.3 1561.41  4990.1 1551.63  4993.1 1549.93  5026.1 1551.63
  5040.3 1554.85  5050.3 1561.66  5091.9 1570.77  5158.9 1576.41  5190.3 1572.06
  5210.3 1575.93  5260.3 1563.59  5310.3 1562.62  5380.3 1572.41  5420.3 1567.62
  5520.3 1574.62  5750.3 1578.46  5800.3 1584.53  5970.3 1621.68  6000.3 1623.90
#Mann=6,-1,0
  2559.0    0.12       0  2619.7    0.05       0  4990.1    0.05       0
  5026.1    0.05       0  5091.9    0.12       0  5158.9    0.05       0
Bank Sta=4990.1,5026.1
Exp/Cntr=0.3,0.1

Type RM Length L Ch R = 1,443702,4465,4465,4465
BEGIN DESCRIPTION:
Clear Fork Brazos Rv 113.0
END DESCRIPTION:
XS GIS Cut Line= 3
      1601465.70      6919574.18      1604661.19      6919143.44
      1605371.18      6918913.44
#Sta/Elev= 30
  1764.9 1594.36  1885.3 1593.19  2117.4 1585.17  2167.8 1585.60  2218.0 1583.51
  2339.3 1572.24  2440.2 1568.87  4074.9 1573.99  4801.4 1573.86  4831.7 1571.59
  4851.9 1566.13  4902.3 1558.42  4952.8 1558.00  4983.1 1546.98  4985.4 1545.28
  5007.9 1545.28  5010.1 1546.98  5014.3 1552.71  5035.3 1560.17  5090.6 1566.01
  5117.3 1573.41  5122.6 1570.88  5186.6 1577.02  5266.6 1588.92  5282.6 1588.57
  5287.8 1590.55  5310.4 1589.13  5392.7 1596.57  5529.4 1597.49  5735.6 1609.19
#Mann=4,-1,0
  1764.9    0.05       0  4983.1    0.07       0  5010.1    0.05       0
  5310.4    0.05       0
Bank Sta=4983.1,5010.1
Exp/Cntr=0.3,0.1

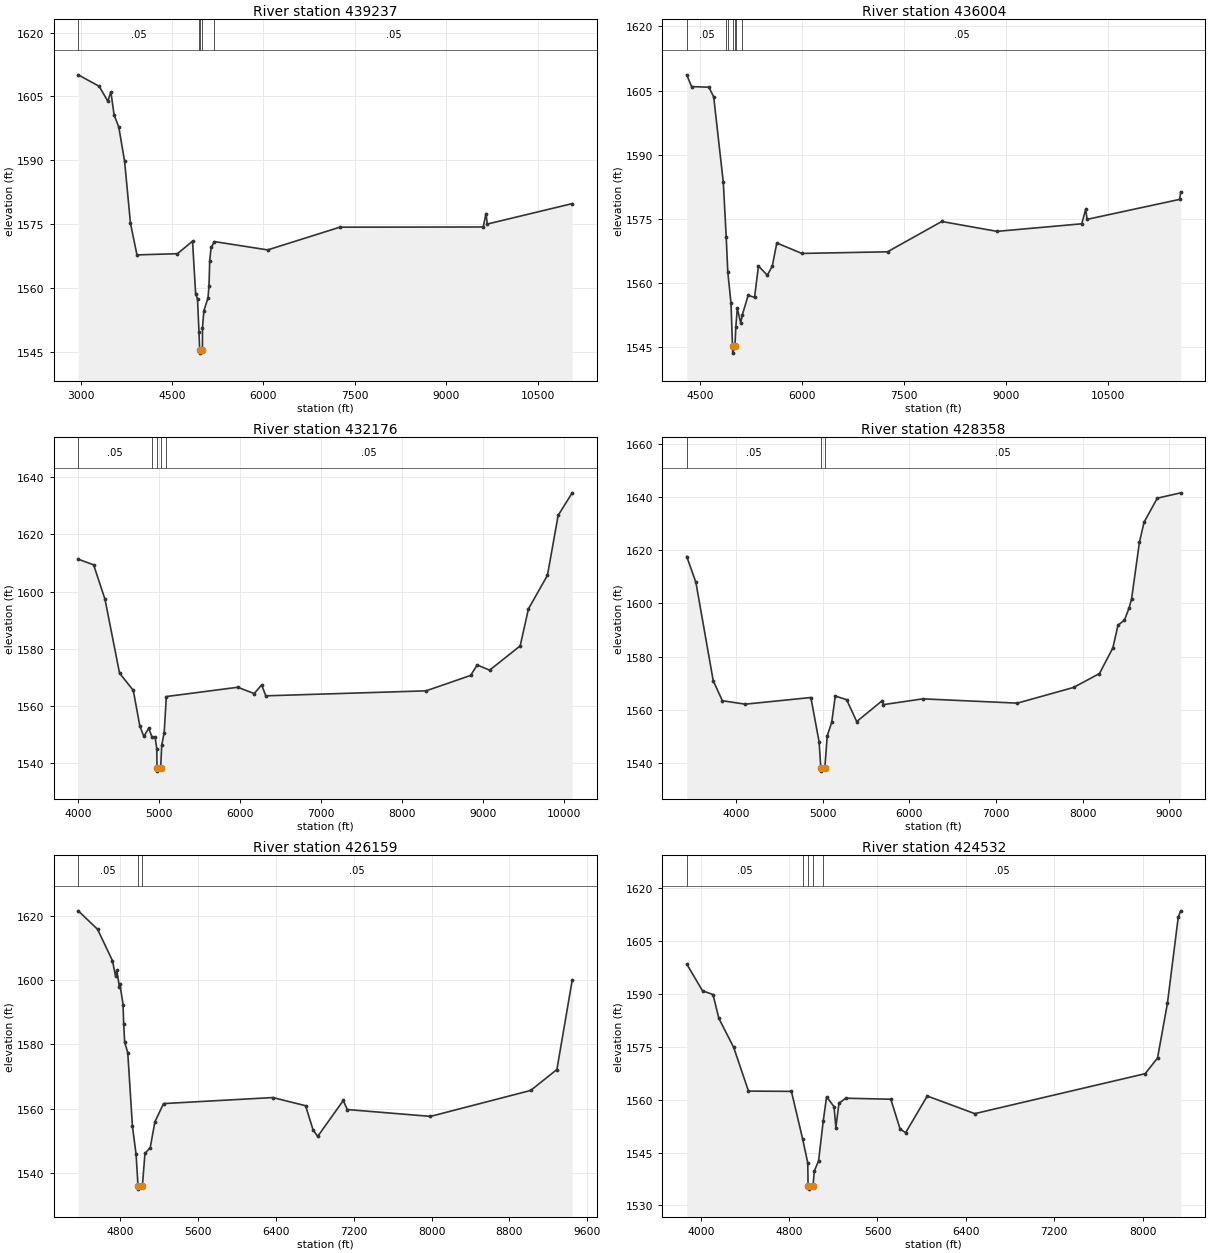
Type RM Length L Ch R = 1,439237,3233,3233,3233
BEGIN DESCRIPTION:
Mapping XS f2b22327
END DESCRIPTION:
XS GIS Cut Line= 3
      1600436.29      6921079.17      1603939.95      6922789.72
      1607729.98      6920963.01
#Sta/Elev= 30
  2962.9 1610.09  3306.4 1607.40  3447.9 1603.90  3498.5 1606.08  3551.3 1600.67
  3628.1 1597.83  3723.8 1589.76  3819.4 1575.24  3926.5 1567.77  4590.8 1568.05
  4838.6 1570.99  4889.2 1558.68  4920.0 1557.38  4944.8 1549.55  4955.9 1545.38
  4959.7 1544.68  5000.9 1545.38  5001.9 1550.67  5024.4 1554.62  5092.0 1557.63
  5108.9 1560.47  5120.3 1566.35  5142.6 1569.51  5198.9 1570.89  6071.7 1568.94
  7256.0 1574.28  9609.4 1574.33  9653.8 1577.49  9676.0 1575.02 11069.1 1579.82
#Mann=5,-1,0
  2962.9    0.05       0  4944.8    0.12       0  4955.9    0.07       0
  5000.9    0.12       0  5198.9    0.05       0
Bank Sta=4955.9,5000.9
Exp/Cntr=0.3,0.1

Type RM Length L Ch R = 1,436004,3828,3828,3828
BEGIN DESCRIPTION:
Clear Fork Brazos Rv 112.0
END DESCRIPTION:
XS GIS Cut Line= 3
      1601654.97      6925238.03      1602155.00      6924738.00
      1607680.03      6921212.98
#Sta/Elev= 30
  4301.7 1608.68  4372.4 1605.93  4627.0 1605.79  4697.7 1603.52  4839.1 1583.52
  4882.1 1570.65  4904.8 1562.63  4952.3 1555.25  4974.2 1545.31  4977.2 1543.61
  5010.2 1545.31  5023.2 1549.74  5044.4 1554.11  5095.2 1550.67  5118.6 1552.56
  5204.3 1557.11  5298.2 1556.66  5355.8 1563.97  5486.1 1561.82  5558.9 1563.97
  5625.7 1569.36  5993.4 1566.92  7252.9 1567.30  8050.0 1574.39  8862.4 1572.08
 10108.0 1573.85 10165.5 1577.26 10186.7 1574.89 11547.3 1579.56 11562.6 1581.34
#Mann=7,-1,0
  4301.7    0.05       0  4882.1    0.12       0  4904.8    0.05       0
  4974.2    0.05       0  5010.2    0.05       0  5023.2    0.12       0
  5118.6    0.05       0
Bank Sta=4974.2,5010.2
Exp/Cntr=0.3,0.1

Type RM Length L Ch R = 1,432176,3818,3818,3818
BEGIN DESCRIPTION:
Clear Fork Brazos Rv 111.0
END DESCRIPTION:
XS GIS Cut Line= 3
      1603555.01      6926838.00      1604555.00      6926838.00
      1609554.99      6927838.00
#Sta/Elev= 30
  4000.0 1611.33  4190.0 1609.35  4330.0 1597.32  4510.0 1571.39  4680.0 1565.34
  4760.0 1552.92  4810.0 1549.19  4870.0 1552.08  4908.8 1549.18  4950.0 1548.84
  4970.0 1544.88  4972.5 1538.05  4976.3 1537.05  5017.5 1538.05  5030.6 1546.09
  5061.2 1550.57  5087.6 1563.19  5968.8 1566.44  6172.8 1564.25  6264.5 1567.28
  6315.5 1563.44  8294.0 1565.19  8844.7 1570.59  8926.2 1574.26  9079.2 1572.44
  9456.5 1580.94  9558.5 1593.91  9793.1 1605.66  9925.6 1626.69 10099.0 1634.59
#Mann=5,-1,0
  4000.0    0.05       0  4908.8    0.12       0  4972.5    0.07       0
  5017.5    0.12       0  5087.6    0.05       0
Bank Sta=4972.5,5017.5
Exp/Cntr=0.3,0.1

Type RM Length L Ch R = 1,428358,2199,2199,2199
BEGIN DESCRIPTION:
Clear Fork Brazos Rv 110.0
END DESCRIPTION:
XS GIS Cut Line= 3
      1604155.03      6929637.99      1605655.00      6929138.00
      1609654.99      6928138.00
#Sta/Elev= 30
  3428.1 1617.62  3533.5 1607.94  3733.8 1570.94  3839.2 1563.42  4102.7 1562.12
  4861.6 1564.62  4956.5 1547.92  4976.9 1537.95  4980.6 1536.95  5021.9 1537.95
  5050.4 1550.19  5102.0 1555.30  5143.2 1565.19  5274.6 1563.80  5390.6 1555.58
  5686.9 1563.47  5699.8 1561.95  6153.4 1564.12  7246.0 1562.51  7895.4 1568.41
  8194.3 1573.64  8348.9 1583.31  8408.2 1591.81  8482.9 1593.73  8537.0 1598.38
  8565.4 1601.81  8655.6 1623.02  8709.7 1630.57  8861.7 1639.55  9132.3 1641.56
#Mann=3,-1,0
  3428.1    0.05       0  4976.9    0.05       0  5021.9    0.05       0
Bank Sta=4976.9,5021.9
Exp/Cntr=0.3,0.1

Type RM Length L Ch R = 1,426159,1627,1627,1627
BEGIN DESCRIPTION:
Mapping XS 10ff3137
END DESCRIPTION:
XS GIS Cut Line= 3
      1604160.26      6931183.35      1605175.91      6930857.83
      1609069.11      6929894.29
#Sta/Elev= 30
  4367.8 1621.50  4566.3 1615.77  4719.3 1606.02  4750.8 1601.25  4764.3 1603.03
  4791.2 1597.74  4796.5 1598.66  4828.6 1592.29  4834.8 1586.36  4845.3 1580.62
  4876.8 1577.39  4925.0 1554.50  4962.4 1545.77  4982.2 1535.96  4985.9 1534.96
  5027.2 1535.96  5053.5 1546.06  5107.9 1547.89  5155.2 1555.83  5244.4 1561.56
  6367.9 1563.44  6704.4 1560.90  6782.1 1553.33  6828.7 1551.35  7092.0 1562.52
  7133.2 1559.71  7988.2 1557.58  9018.4 1565.65  9287.6 1572.15  9445.0 1599.93
#Mann=3,-1,0
  4367.8    0.05       0  4982.2    0.05       0  5027.2    0.05       0
Bank Sta=4982.2,5027.2
Exp/Cntr=0.3,0.1

Type RM Length L Ch R = 1,424532,3412,3412,3412
BEGIN DESCRIPTION:
Clear Fork Brazos Rv 109.0
END DESCRIPTION:
XS GIS Cut Line= 3
      1605104.97      6932288.01      1606105.00      6931788.00
      1609105.03      6930287.98
#Sta/Elev= 30
  3873.3 1598.51  4015.9 1590.93  4110.9 1589.86  4164.0 1583.10  4298.2 1574.84
  4432.3 1562.44  4820.9 1562.36  4923.0 1548.78  4969.0 1542.06  4971.8 1535.60
  4975.6 1534.60  5016.8 1535.60  5027.7 1539.73  5066.8 1542.61  5109.0 1553.95
  5139.5 1560.82  5206.6 1558.03  5223.4 1552.10  5251.3 1558.98  5312.8 1560.42
  5720.9 1560.13  5804.7 1551.68  5855.0 1550.62  6050.7 1561.04  6481.1 1556.04
  8024.0 1567.39  8135.8 1571.85  8225.3 1587.39  8323.1 1611.84  8345.5 1613.63
#Mann=5,-1,0
  3873.3    0.05       0  4923.0     0.1       0  4971.8    0.07       0
  5016.8     0.1       0  5109.0    0.05       0
Bank Sta=4971.8,5016.8
Exp/Cntr=0.3,0.1

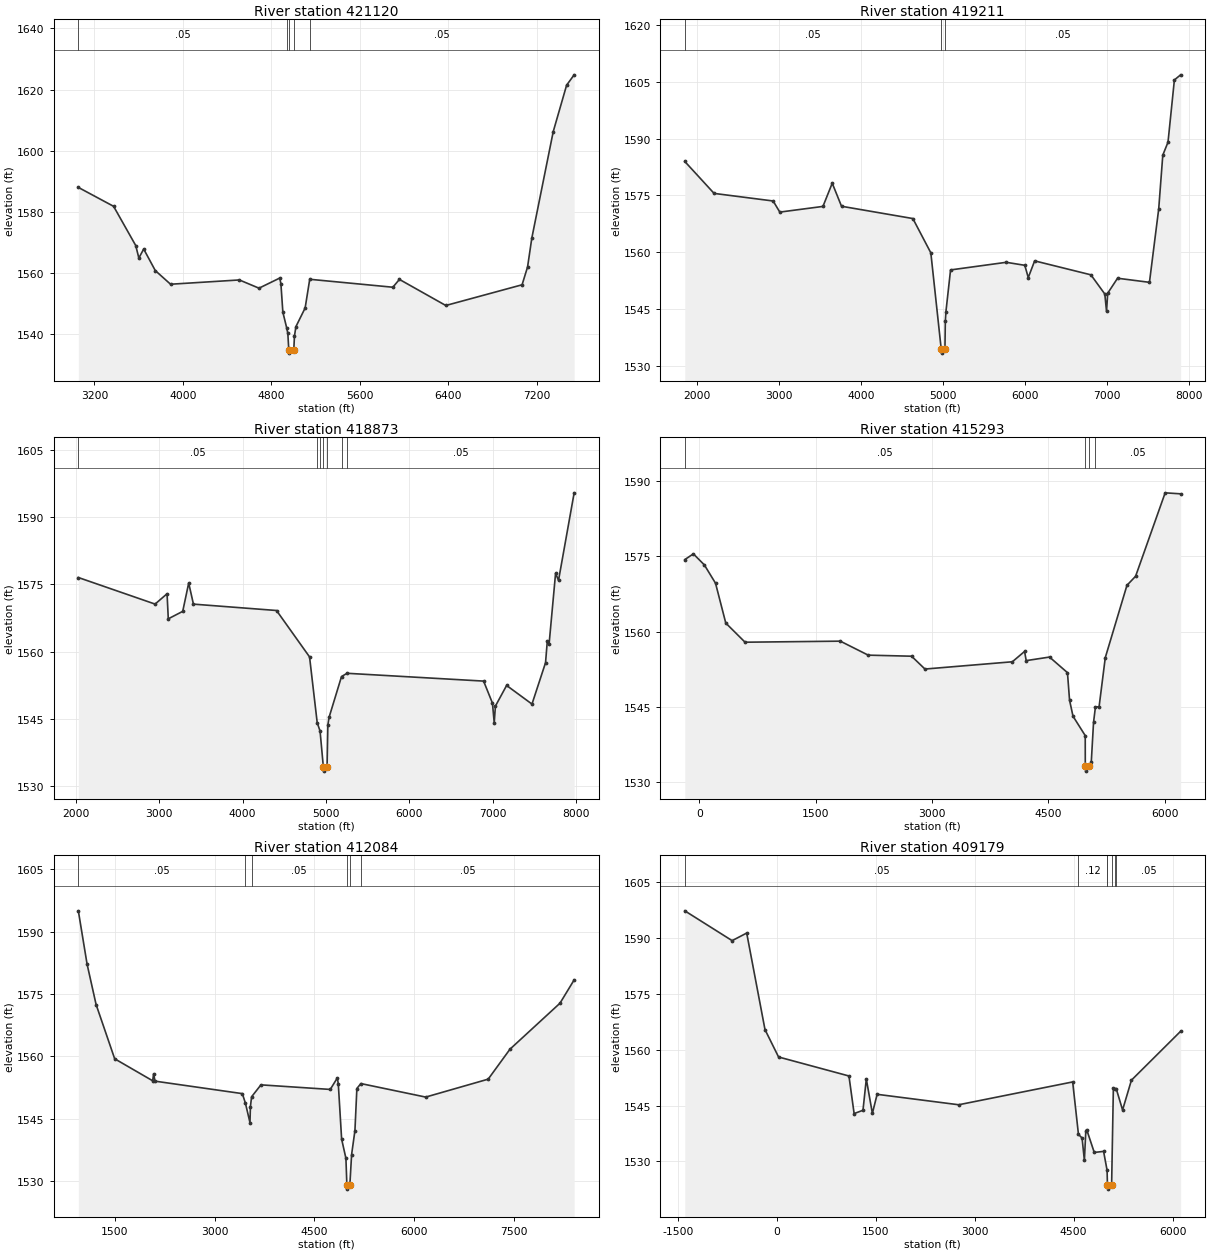
Type RM Length L Ch R = 1,421120,1909,1909,1909
BEGIN DESCRIPTION:
Mapping XS f5c1fc0f
END DESCRIPTION:
XS GIS Cut Line= 2
      1606139.42      6934659.92      1610436.35      6933383.86
#Sta/Elev= 30
  3054.0 1588.01  3372.8 1581.83  3573.1 1569.00  3601.1 1564.92  3644.8 1567.87
  3749.6 1560.83  3887.7 1556.36  4509.8 1557.76  4687.2 1555.07  4875.0 1558.38
  4885.4 1556.47  4903.0 1547.23  4937.6 1542.09  4947.9 1540.30  4956.7 1534.84
  4960.5 1533.84  5001.7 1534.84  5007.8 1539.40  5021.0 1542.50  5104.4 1548.60
  5145.9 1557.98  5897.2 1555.38  5956.7 1557.94  6376.0 1549.41  7065.6 1556.18
  7115.2 1562.01  7153.6 1571.44  7347.2 1606.25  7468.2 1621.43  7536.4 1624.81
#Mann=5,-1,0
  3054.0    0.05       0  4937.6    0.12       0  4956.7    0.07       0
  5001.7    0.12       0  5145.9    0.05       0
Bank Sta=4956.7,5001.7
Exp/Cntr=0.3,0.1

Type RM Length L Ch R = 1,419211,338,338,338
BEGIN DESCRIPTION:
Mapping XS 97556a4c
END DESCRIPTION:
XS GIS Cut Line= 4
      1605853.03      6937146.88      1607376.43      6936886.47
      1608860.80      6935467.20      1610591.31      6933736.70
#Sta/Elev= 30
  1849.3 1583.96  2206.4 1575.54  2926.7 1573.54  3007.8 1570.61  3534.1 1572.11
  3647.3 1578.23  3760.5 1572.15  4630.4 1568.91  4849.6 1559.87  4976.6 1534.42
  4980.3 1533.42  5021.6 1534.42  5026.4 1541.85  5033.6 1544.34  5090.2 1555.36
  5769.1 1557.37  5995.4 1556.58  6037.8 1553.34  6115.6 1557.75  6801.5 1554.07
  6971.2 1549.01  6992.4 1544.43  7006.5 1549.22  7126.7 1553.17  7515.7 1552.09
  7628.8 1571.50  7678.3 1585.62  7741.9 1589.05  7819.7 1605.46  7895.8 1606.81
#Mann=3,-1,0
  1849.3    0.05       0  4976.6    0.03       0  5021.6    0.05       0
Bank Sta=4976.6,5021.6
Exp/Cntr=0.3,0.1

Type RM Length L Ch R = 1,418873,3580,3580,3580
BEGIN DESCRIPTION:
Mapping XS 89ec0814
END DESCRIPTION:
XS GIS Cut Line= 5
      1607024.87      6938396.88      1607389.45      6937550.53
      1607858.20      6936873.45      1609173.30      6935636.47
      1610904.95      6933982.95
#Sta/Elev= 30
  2029.6 1576.49  2949.8 1570.57  3093.4 1572.87  3108.2 1567.29  3281.2 1568.95
  3352.8 1575.26  3409.6 1570.56  4405.8 1569.14  4801.9 1558.80  4893.6 1544.14
  4927.9 1542.28  4966.9 1534.35  4970.6 1533.35  5012.0 1534.35  5021.2 1543.59
  5035.3 1545.30  5185.0 1554.42  5251.3 1555.15  6888.7 1553.41  6994.7 1548.51
  7016.1 1544.13  7030.2 1547.84  7164.5 1552.44  7468.7 1548.29  7631.3 1557.51
  7652.7 1562.38  7673.7 1561.63  7751.7 1577.43  7786.9 1575.85  7974.4 1595.36
#Mann=7,-1,0
  2029.6    0.05       0  4893.6    0.12       0  4927.9    0.05       0
  4966.9    0.03       0  5012.0    0.05       0  5185.0    0.12       0
  5251.3    0.05       0
Bank Sta=4966.9,5012
Exp/Cntr=0.3,0.1

Type RM Length L Ch R = 1,415293,3209,3209,3209
BEGIN DESCRIPTION:
Mapping XS 9ecf8570
END DESCRIPTION:
XS GIS Cut Line= 4
      1607239.98      6938318.40      1609010.86      6937888.70
      1612187.94      6935649.12      1612396.27      6934998.11
#Sta/Elev= 30
  -189.2 1574.37   -78.7 1575.51    62.9 1573.31   207.0 1569.66   339.1 1561.72
   587.7 1557.90  1816.0 1558.11  2175.7 1555.32  2734.8 1555.11  2907.2 1552.55
  4034.1 1554.00  4191.7 1556.06  4212.6 1554.23  4513.3 1554.94  4744.7 1551.83
  4771.7 1546.33  4816.1 1543.15  4973.8 1539.28  4974.6 1533.20  4979.1 1532.20
  5028.6 1533.20  5051.6 1533.98  5080.9 1541.91  5105.3 1545.00  5152.3 1545.01
  5232.4 1554.83  5511.9 1569.25  5623.2 1571.05  6004.3 1587.68  6203.7 1587.48
#Mann=4,-1,0
  -189.2    0.05       0  4974.6    0.07       0  5028.6    0.05       0
  5105.3    0.05       0
Bank Sta=4974.6,5028.6
Exp/Cntr=0.3,0.1

Type RM Length L Ch R = 1,412084,2905,2905,2905
BEGIN DESCRIPTION:
Mapping XS 52815245
END DESCRIPTION:
XS GIS Cut Line= 3
      1608574.31      6940701.60      1613001.43      6937420.33
      1613235.64      6935481.56
#Sta/Elev= 30
   948.8 1595.00  1080.6 1582.17  1216.2 1572.47  1495.9 1559.43  2067.7 1554.14
  2082.3 1555.84  2103.1 1554.05  3417.8 1551.05  3464.8 1548.70  3532.6 1544.07
  3538.8 1547.90  3557.2 1550.30  3697.5 1553.16  4740.9 1552.06  4847.3 1554.82
  4861.9 1553.40  4912.0 1540.12  4976.7 1535.50  4990.9 1529.09  4994.6 1528.09
  5035.9 1529.09  5062.2 1536.40  5112.3 1542.16  5141.5 1552.28  5201.9 1553.47
  6177.5 1550.22  7118.0 1554.53  7445.9 1561.73  8198.8 1572.79  8412.2 1578.40
#Mann=6,-1,0
   948.8    0.05       0  3464.8    0.12       0  3557.2    0.05       0
  4990.9    0.05       0  5035.9    0.05       0  5201.9    0.05       0
Bank Sta=4990.9,5035.9
Exp/Cntr=0.3,0.1

Type RM Length L Ch R = 1,409179,3420,3420,3420
BEGIN DESCRIPTION:
Clear Fork Brazos Rv 105.0
END DESCRIPTION:
XS GIS Cut Line= 3
      1610204.99      6944388.01      1614205.00      6939388.00
      1615205.03      6938887.99
#Sta/Elev= 30
 -1398.5 1597.37  -680.5 1589.35  -459.6 1591.39  -181.9 1565.42    23.8 1558.06
  1091.5 1552.95  1170.0 1542.84  1304.4 1543.73  1354.9 1552.14  1446.9 1542.90
  1518.9 1548.02  2756.3 1545.21  4485.2 1551.35  4573.0 1537.22  4627.7 1536.28
  4662.9 1530.24  4684.5 1538.20  4698.1 1538.51  4812.5 1532.39  4954.2 1532.67
  5007.3 1527.58  5012.8 1523.52  5018.1 1522.52  5075.8 1523.52  5102.5 1549.70
  5123.2 1549.55  5148.6 1549.36  5242.2 1543.81  5376.4 1551.82  6122.7 1564.97
#Mann=7,-1,0
 -1398.5    0.05       0  4573.0    0.12       0  5007.3    0.05       0
  5012.8    0.07       0  5075.8    0.05       0  5123.2    0.12       0
  5148.6    0.05       0
Bank Sta=5012.8,5075.8
Exp/Cntr=0.3,0.1

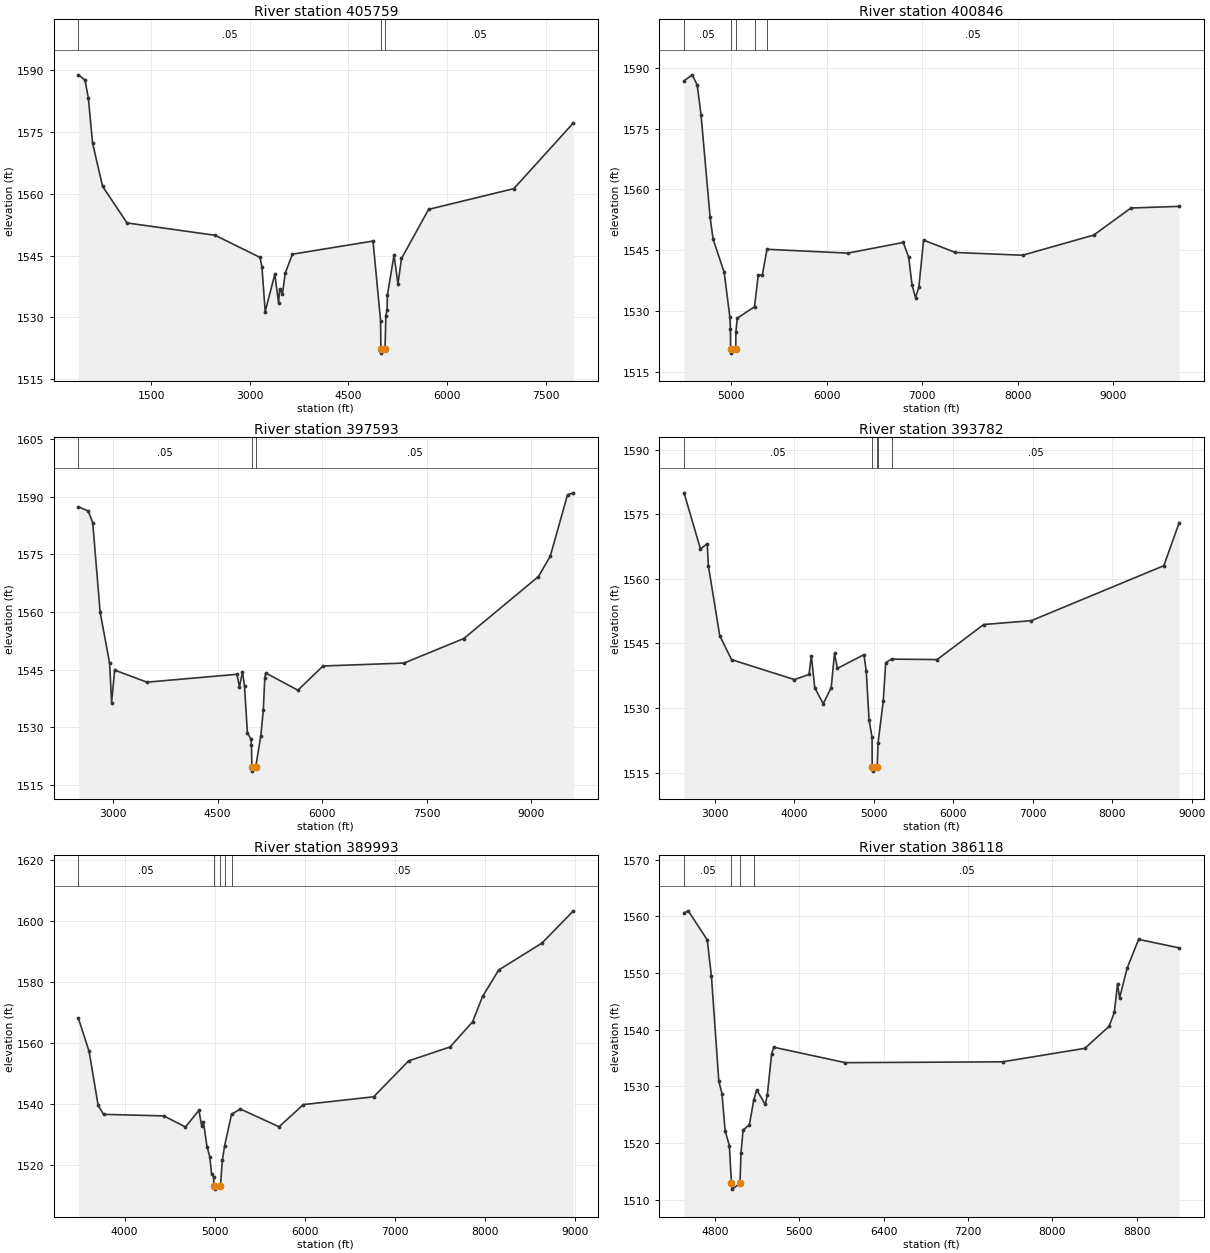
Type RM Length L Ch R = 1,405759,4913,4913,4913
BEGIN DESCRIPTION:
Clear Fork Brazos Rv 104.0
END DESCRIPTION:
XS GIS Cut Line= 3
      1611555.00      6944438.00      1615507.96      6941968.07
      1618161.68      6940866.86
#Sta/Elev= 30
   390.3 1588.76   492.3 1587.52   543.6 1583.09   607.9 1572.20   760.0 1561.76
  1131.5 1552.90  2473.6 1549.90  3155.2 1544.55  3184.9 1542.21  3234.2 1531.44
  3380.5 1540.46  3438.3 1533.48  3453.6 1536.87  3496.0 1535.62  3538.7 1540.73
  3648.2 1545.33  4874.7 1548.51  4990.2 1529.19  4994.8 1522.37  5000.1 1521.37
  5057.8 1522.37  5070.0 1530.36  5088.5 1531.79  5093.9 1535.47  5194.8 1545.13
  5254.0 1538.10  5308.1 1544.29  5721.0 1556.18  7017.4 1561.20  7924.6 1577.13
#Mann=3,-1,0
   390.3    0.05       0  4994.8    0.05       0  5057.8    0.05       0
Bank Sta=4994.8,5057.8
Exp/Cntr=0.3,0.1

Type RM Length L Ch R = 1,400846,3253,3253,3253
BEGIN DESCRIPTION:
Mapping XS 07d09aaa
END DESCRIPTION:
XS GIS Cut Line= 3
      1614213.44      6946111.75      1614321.96      6945699.41
      1617946.06      6942617.83
#Sta/Elev= 30
  4506.5 1586.79  4593.1 1588.27  4644.8 1585.74  4685.2 1578.23  4779.2 1553.18
  4811.4 1547.65  4927.2 1539.50  4985.9 1528.53  4992.5 1525.43  4994.2 1520.56
  4998.7 1519.56  5048.2 1520.56  5049.6 1524.84  5063.9 1528.19  5244.5 1531.01
  5283.6 1538.83  5326.4 1538.87  5375.4 1545.20  6220.4 1544.25  6801.3 1546.88
  6858.4 1543.22  6893.6 1536.40  6929.8 1533.26  6965.0 1535.86  7014.4 1547.46
  7348.3 1544.41  8050.0 1543.73  8795.8 1548.71  9185.6 1555.39  9690.0 1555.79
#Mann=5,-1,0
  4506.5    0.05       0  4994.2    0.05       0  5048.2    0.05       0
  5244.5    0.12       0  5375.4    0.05       0
Bank Sta=4994.2,5048.2
Exp/Cntr=0.3,0.1

Type RM Length L Ch R = 1,397593,3811,3811,3811
BEGIN DESCRIPTION:
Clear Fork Brazos Rv 102.0
END DESCRIPTION:
XS GIS Cut Line= 3
      1615254.96      6947488.03      1617255.00      6945988.00
      1620254.99      6942488.01
#Sta/Elev= 30
  2499.2 1587.39  2642.0 1586.27  2706.5 1583.20  2812.8 1559.94  2949.2 1546.61
  2977.4 1536.42  3021.1 1544.86  3485.7 1541.72  4777.4 1543.77  4812.8 1540.50
  4856.5 1544.37  4885.7 1540.76  4927.4 1528.60  4977.4 1526.85  4985.7 1525.26
  4991.8 1519.56  4996.3 1518.56  5045.8 1519.56  5119.4 1527.69  5155.7 1534.42
  5176.5 1542.71  5190.8 1544.11  5651.7 1539.63  6013.4 1545.93  7176.3 1546.69
  8034.6 1553.08  9105.8 1569.21  9275.9 1574.51  9524.0 1590.49  9609.0 1591.01
#Mann=3,-1,0
  2499.2    0.05       0  4991.8    0.05       0  5045.8    0.05       0
Bank Sta=4991.8,5045.8
Exp/Cntr=0.3,0.1

Type RM Length L Ch R = 1,393782,3789,3789,3789
BEGIN DESCRIPTION:
Mapping XS cce6b25b
END DESCRIPTION:
XS GIS Cut Line= 3
      1619009.43      6949692.50      1620474.30      6947836.99
      1621353.08      6944072.35
#Sta/Elev= 30
  2612.4 1580.01  2819.4 1566.97  2904.3 1568.19  2918.7 1563.08  3061.4 1546.84
  3210.5 1541.24  4000.9 1536.61  4185.2 1537.79  4214.1 1542.16  4257.4 1534.72
  4363.6 1530.99  4464.2 1534.74  4505.8 1542.72  4542.0 1539.21  4876.2 1542.39
  4905.0 1538.61  4940.3 1527.29  4978.5 1523.17  4980.0 1516.33  4985.2 1515.33
  5043.0 1516.33  5053.2 1521.82  5119.2 1531.59  5150.0 1540.54  5224.3 1541.36
  5797.7 1541.26  6382.3 1549.40  6982.1 1550.30  8649.7 1563.08  8842.3 1573.07
#Mann=5,-1,0
  2612.4    0.05       0  4980.0    0.05       0  5043.0    0.05       0
  5053.2    0.12       0  5224.3    0.05       0
Bank Sta=4980,5043
Exp/Cntr=0.3,0.1

Type RM Length L Ch R = 1,389993,3875,3875,3875
BEGIN DESCRIPTION:
Clear Fork Brazos Rv 100.0
END DESCRIPTION:
XS GIS Cut Line= 3
      1619704.98      6950588.00      1621205.00      6950588.00
      1625204.98      6950588.00
#Sta/Elev= 30
  3484.9 1568.17  3604.9 1557.21  3704.9 1539.63  3764.9 1536.61  4434.9 1536.10
  4674.9 1532.46  4824.9 1537.94  4854.9 1532.86  4874.9 1534.09  4914.9 1525.97
  4944.9 1522.80  4964.9 1517.15  4987.4 1516.18  4991.9 1513.12  4997.9 1512.12
  5063.9 1513.12  5084.9 1521.59  5109.9 1526.24  5186.7 1536.63  5284.9 1538.35
  5714.9 1532.54  5984.9 1539.80  6764.9 1542.35  7154.9 1554.12  7614.9 1558.68
  7864.9 1566.91  7974.9 1575.19  8154.9 1583.87  8634.9 1592.67  8984.9 1603.24
#Mann=5,-1,0
  3484.9    0.05       0  4991.9    0.05       0  5063.9    0.05       0
  5109.9    0.12       0  5186.7    0.05       0
Bank Sta=4991.9,5063.9
Exp/Cntr=0.3,0.1

Type RM Length L Ch R = 1,386118,2460,2460,2460
BEGIN DESCRIPTION:
Clear Fork Brazos Rv 99.0
END DESCRIPTION:
XS GIS Cut Line= 3
      1619504.97      6953938.00      1620005.00      6953938.00
      1624199.40      6953838.73
#Sta/Elev= 30
  4506.4 1560.60  4546.4 1560.98  4726.4 1555.87  4766.4 1549.42  4836.4 1530.92
  4866.4 1528.71  4896.4 1522.15  4936.4 1519.54  4956.3 1512.86  4963.0 1511.86
  5037.3 1512.86  5046.4 1518.16  5066.4 1522.28  5126.5 1523.22  5168.3 1527.67
  5196.5 1529.35  5276.5 1526.81  5296.5 1528.46  5336.5 1535.65  5356.5 1536.91
  6036.7 1534.18  7527.1 1534.33  8307.4 1536.71  8537.4 1540.59  8587.4 1543.05
  8617.4 1548.09  8637.4 1545.62  8707.5 1550.81  8817.5 1555.94  9202.0 1554.44
#Mann=4,-1,0
  4506.4    0.05       0  4956.3    0.07       0  5037.3    0.05       0
  5168.3    0.05       0
Bank Sta=4956.3,5037.3
Exp/Cntr=0.3,0.1