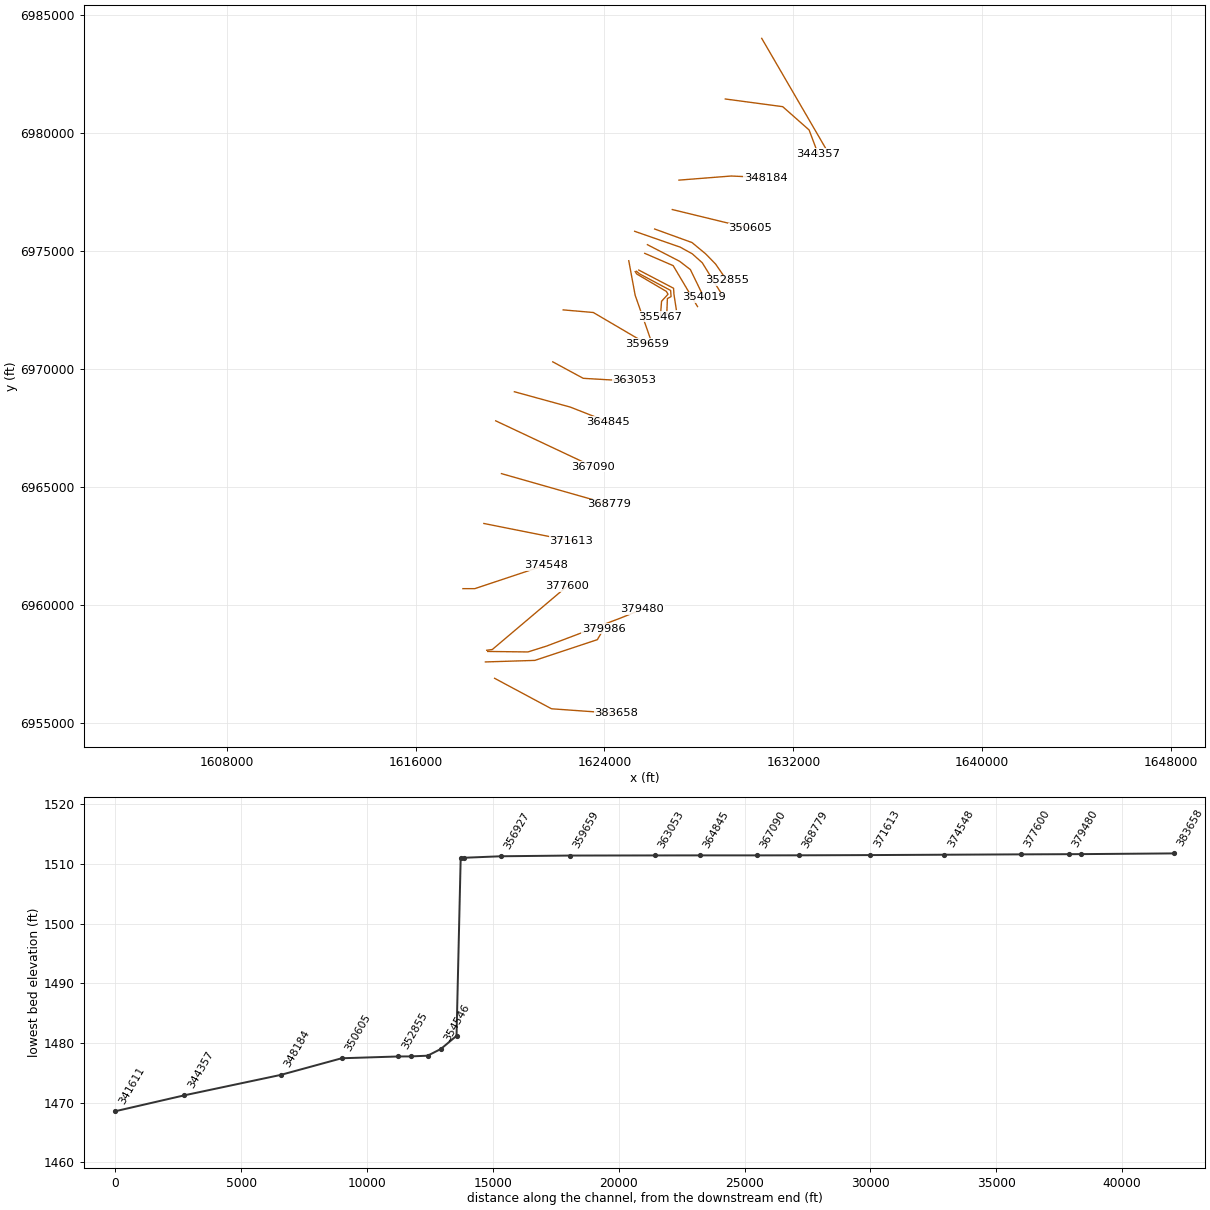
HEC-RAS study Clear Fork Brazos Rv.prj: Clear Fork Brazos Rv Base Level Engineering

--- Clear Fork Brazos Rv.g01 (geometry) --- (continued)

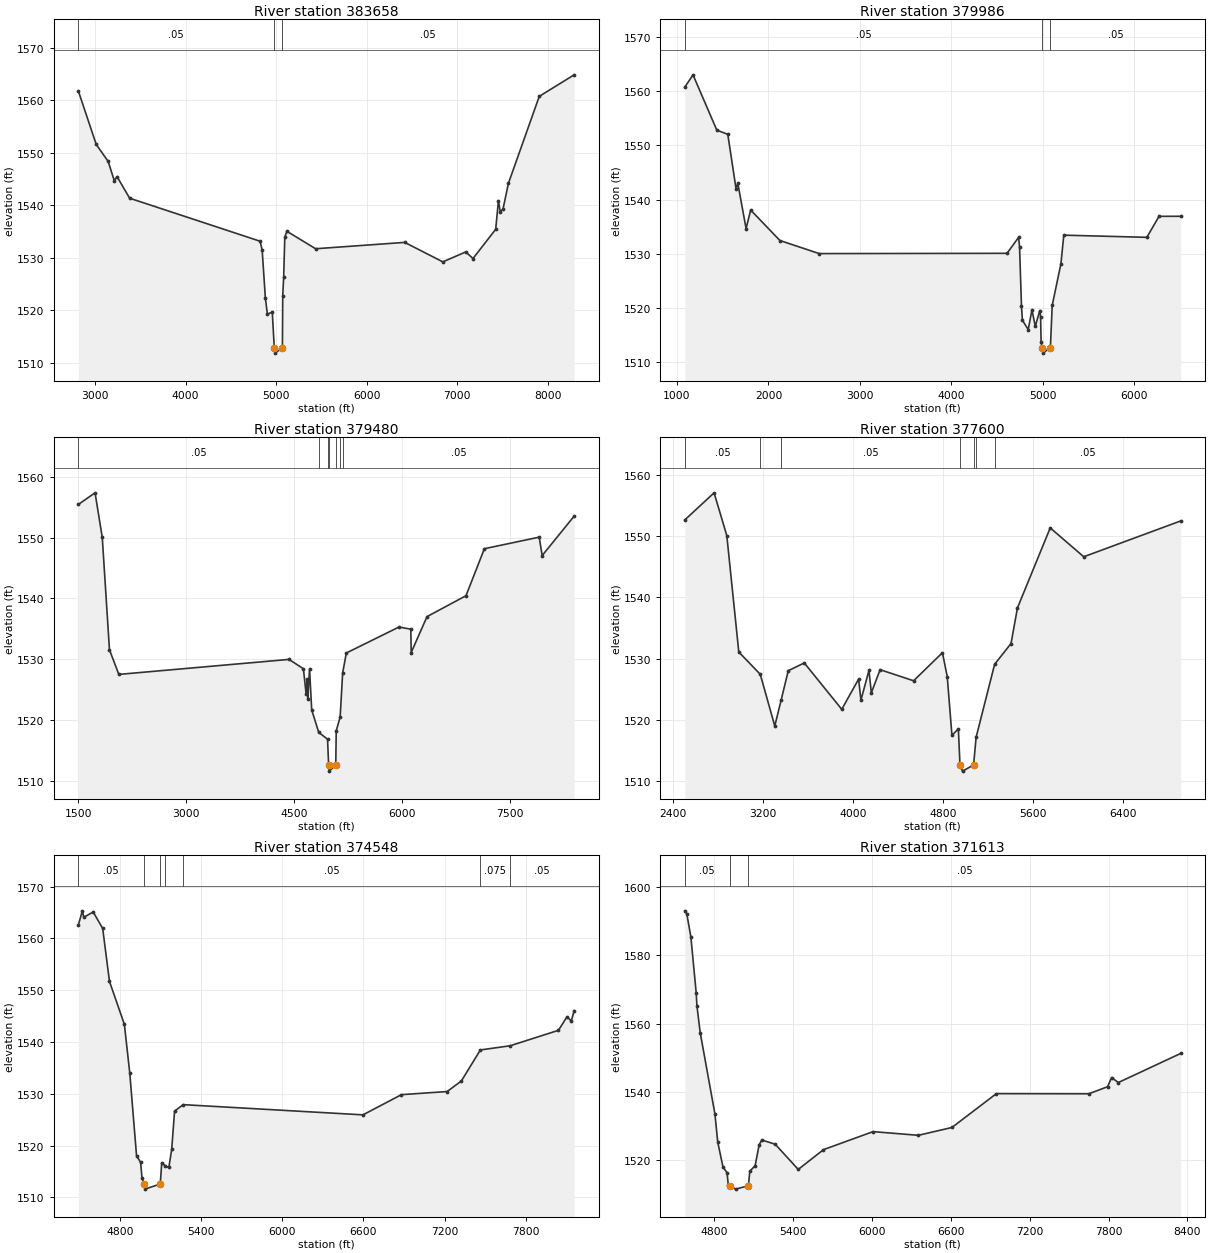
Type RM Length L Ch R = 1,383658,3672,3672,3672
BEGIN DESCRIPTION:
Mapping XS d5714d4a
END DESCRIPTION:
XS GIS Cut Line= 3
      1619345.81      6956886.48      1621754.68      6955595.24
      1624489.09      6955399.92
#Sta/Elev= 30
  2815.1 1561.76  3012.8 1551.56  3144.4 1548.34  3211.3 1544.69  3242.7 1545.43
  3381.5 1541.32  4822.4 1533.12  4845.1 1531.38  4880.2 1522.31  4902.2 1519.25
  4956.6 1519.60  4978.5 1512.80  4986.0 1511.80  5068.5 1512.80  5072.0 1522.75
  5082.5 1526.36  5094.7 1533.88  5117.4 1535.02  5435.1 1531.69  6418.8 1532.90
  6839.8 1529.19  7092.5 1531.08  7172.7 1529.83  7423.3 1535.40  7453.4 1540.82
  7473.4 1538.74  7503.5 1539.20  7563.7 1544.15  7904.5 1560.73  8289.6 1564.83
#Mann=3,-1,0
  2815.1    0.05       0  4978.5    0.05       0  5068.5    0.05       0
Bank Sta=4978.5,5068.5
Exp/Cntr=0.3,0.1

Type RM Length L Ch R = 1,379986,506,506,506
BEGIN DESCRIPTION:
Mapping XS 789bc0a7
END DESCRIPTION:
XS GIS Cut Line= 4
      1618955.15      6957580.92      1621049.39      6957646.02
      1623696.96      6958524.93      1623968.92      6958987.98
#Sta/Elev= 30
  1085.2 1560.72  1175.1 1562.99  1435.2 1552.79  1555.3 1552.02  1645.3 1542.01
  1665.3 1542.97  1755.4 1534.64  1805.4 1538.06  2125.5 1532.44  2555.8 1530.03
  4608.8 1530.08  4735.2 1533.02  4745.8 1531.30  4766.9 1520.29  4777.4 1517.74
  4840.6 1516.02  4881.1 1519.65  4918.1 1516.63  4967.0 1519.53  4976.2 1518.43
  4981.4 1513.76  4993.1 1512.68  5000.6 1511.68  5083.1 1512.68  5102.9 1520.50
  5197.9 1528.13  5229.6 1533.43  6137.9 1533.03  6270.8 1536.90  6507.1 1536.91
#Mann=3,-1,0
  1085.2    0.05       0  4993.1    0.05       0  5083.1    0.05       0
Bank Sta=4993.1,5083.1
Exp/Cntr=0.3,0.1

Type RM Length L Ch R = 1,379480,1880,1880,1880
BEGIN DESCRIPTION:
Mapping XS b1b49d0a
END DESCRIPTION:
XS GIS Cut Line= 5
      1619052.84      6958025.80      1620756.42      6958004.09
      1621548.52      6958253.66      1624640.97      6959425.53
      1625606.71      6959816.17
#Sta/Elev= 30
  1504.4 1555.42  1736.6 1557.33  1836.6 1550.02  1936.6 1531.58  2066.6 1527.54
  4428.5 1530.00  4628.9 1528.47  4665.8 1524.40  4683.8 1526.74  4689.2 1523.52
  4714.0 1528.43  4744.1 1521.72  4841.7 1518.02  4964.1 1516.91  4979.0 1512.67
  4987.2 1511.67  5078.0 1512.67  5084.5 1518.27  5139.0 1520.56  5173.7 1527.77
  5224.6 1531.05  5955.0 1535.31  6119.9 1534.96  6125.3 1531.13  6344.7 1537.02
  6885.9 1540.45  7141.2 1548.16  7902.2 1550.06  7943.3 1547.04  8387.4 1553.51
#Mann=7,-1,0
  1504.4    0.05       0  4841.7    0.12       0  4964.1    0.05       0
  4979.0    0.03       0  5078.0    0.05       0  5139.0    0.12       0
  5173.7    0.05       0
Bank Sta=4979,5078
Exp/Cntr=0.3,0.1

Type RM Length L Ch R = 1,377600,3052,3052,3052
BEGIN DESCRIPTION:
Mapping XS 202e3365
END DESCRIPTION:
XS GIS Cut Line= 3
      1619009.75      6958075.33      1619248.49      6958107.89
      1622427.78      6960798.89
#Sta/Elev= 30
  2504.9 1552.62  2765.1 1557.04  2878.2 1550.07  2984.8 1531.07  3175.4 1527.44
  3304.5 1519.00  3361.3 1523.24  3424.2 1528.02  3566.7 1529.29  3899.9 1521.72
  4049.4 1526.65  4070.2 1523.23  4141.7 1528.07  4162.5 1524.41  4240.5 1528.19
  4538.2 1526.38  4794.3 1530.96  4837.1 1527.07  4878.8 1517.49  4936.0 1518.51
  4950.3 1512.64  4972.8 1511.64  5071.1 1512.64  5093.8 1517.17  5258.3 1529.07
  5404.0 1532.46  5461.1 1538.27  5752.3 1551.32  6050.0 1546.61  6911.1 1552.45
#Mann=7,-1,0
  2504.9    0.05       0  3175.4    0.12       0  3361.3    0.05       0
  4950.3    0.03       0  5071.1    0.05       0  5093.8    0.12       0
  5258.3    0.05       0
Bank Sta=4950.3,5071.1
Exp/Cntr=0.3,0.1

Type RM Length L Ch R = 1,374548,2935,2935,2935
BEGIN DESCRIPTION:
Clear Fork Brazos Rv 96.0
END DESCRIPTION:
XS GIS Cut Line= 3
      1618005.00      6960688.00      1618505.00      6960688.00
      1621505.02      6961688.01
#Sta/Elev= 30
  4494.3 1562.56  4524.3 1565.31  4534.3 1564.06  4604.3 1565.08  4674.3 1561.90
  4724.3 1551.68  4834.3 1543.40  4874.3 1533.97  4924.3 1518.03  4954.3 1516.74
  4964.3 1513.79  4979.3 1512.58  4986.8 1511.58  5099.7 1512.58  5110.3 1516.68
  5136.2 1516.05  5163.0 1515.76  5184.0 1519.28  5205.1 1526.63  5268.6 1527.89
  6596.5 1525.92  6881.1 1529.82  7218.4 1530.42  7323.8 1532.47  7463.9 1538.45
  7684.2 1539.26  8040.6 1542.24  8103.9 1544.86  8135.5 1544.04  8156.6 1546.02
#Mann=7,-1,0
  4494.3    0.05       0  4979.3    0.05       0  5099.7    0.05       0
  5136.2    0.12       0  5268.6    0.05       0  7463.9   0.075       0
  7684.2    0.05       0
Bank Sta=4979.3,5099.7
Exp/Cntr=0.3,0.1

Type RM Length L Ch R = 1,371613,2834,2834,2834
BEGIN DESCRIPTION:
Mapping XS 30701db5
END DESCRIPTION:
XS GIS Cut Line= 2
      1618890.05      6963451.15      1622590.10      6962713.31
#Sta/Elev= 30
  4575.7 1593.02  4590.9 1592.12  4622.0 1585.35  4662.3 1569.05  4668.0 1565.22
  4692.9 1557.34  4805.1 1533.51  4826.2 1525.33  4866.3 1517.99  4896.9 1516.37
  4907.0 1512.61  4917.2 1512.52  4962.5 1511.52  5060.0 1512.52  5070.2 1516.74
  5111.0 1518.40  5141.6 1524.52  5162.0 1525.91  5263.9 1524.66  5439.0 1517.29
  5631.0 1523.08  6008.3 1528.36  6352.9 1527.28  6608.2 1529.57  6946.4 1539.48
  7650.0 1539.44  7792.8 1541.51  7823.4 1544.20  7874.3 1542.73  8348.6 1551.25
#Mann=3,-1,0
  4575.7    0.05       0  4917.2    0.03       0  5060.0    0.05       0
Bank Sta=4917.2,5060
Exp/Cntr=0.3,0.1

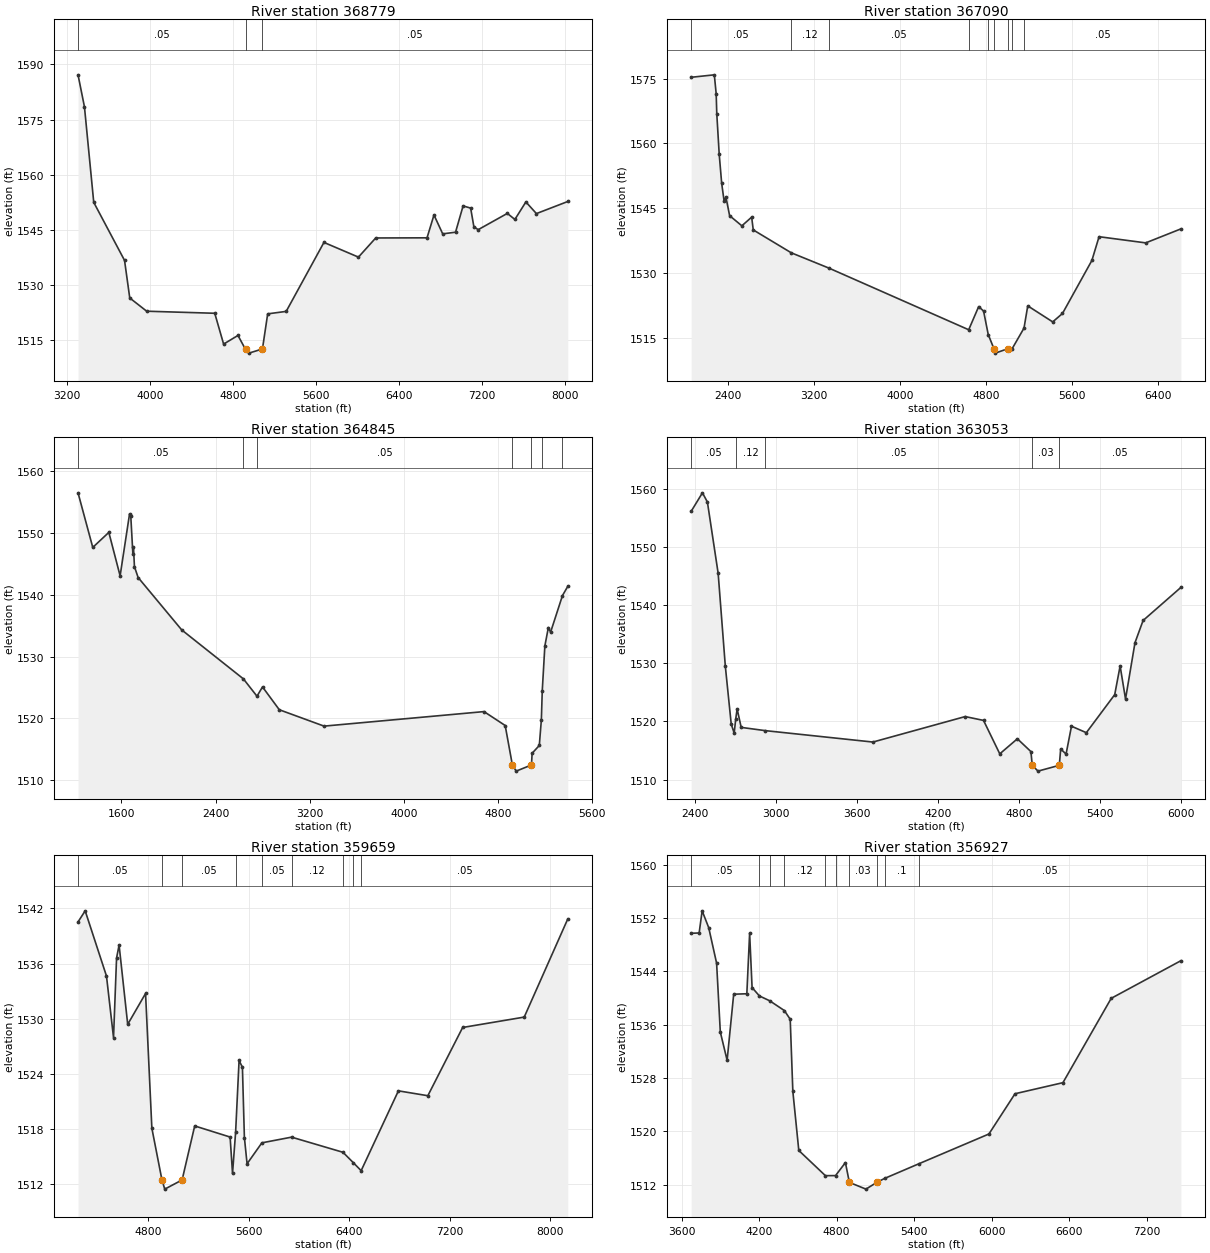
Type RM Length L Ch R = 1,368779,1689,1689,1689
BEGIN DESCRIPTION:
Mapping XS b5058aa9
END DESCRIPTION:
XS GIS Cut Line= 2
      1619635.50      6965564.87      1624175.45      6964271.46
#Sta/Elev= 30
  3306.0 1587.17  3367.9 1578.47  3457.5 1552.48  3754.3 1536.70  3804.6 1526.48
  3967.8 1522.88  4623.8 1522.32  4709.2 1513.94  4847.6 1516.29  4920.5 1512.48
  4953.0 1511.48  5083.5 1512.61  5134.0 1522.16  5312.3 1522.83  5676.2 1541.59
  6008.7 1537.59  6175.3 1542.80  6669.9 1542.84  6736.8 1549.05  6820.9 1543.92
  6944.7 1544.37  7017.5 1551.52  7090.3 1550.92  7121.5 1545.83  7163.1 1545.06
  7443.8 1549.48  7516.6 1547.84  7622.7 1552.60  7724.2 1549.43  8026.6 1552.72
#Mann=3,-1,0
  3306.0    0.05       0  4920.5    0.03       0  5083.5    0.05       0
Bank Sta=4920.5,5083.5
Exp/Cntr=0.3,0.1

Type RM Length L Ch R = 1,367090,2245,2245,2245
BEGIN DESCRIPTION:
Clear Fork Brazos Rv 94.0
END DESCRIPTION:
XS GIS Cut Line= 2
      1619392.50      6967803.57      1623513.94      6965862.16
#Sta/Elev= 30
  2059.0 1575.32  2274.4 1575.89  2291.7 1571.51  2297.2 1566.90  2320.0 1557.46
  2342.8 1550.78  2365.6 1546.63  2382.3 1547.60  2416.7 1543.29  2530.6 1540.94
  2621.8 1542.95  2636.6 1539.99  2990.5 1534.69  3341.6 1531.14  4640.7 1516.88
  4733.4 1522.24  4779.0 1521.21  4822.4 1515.77  4875.7 1512.47  4888.2 1511.47
  5002.1 1512.47  5044.2 1512.47  5155.2 1517.27  5190.0 1522.41  5422.2 1518.70
  5513.0 1520.65  5786.5 1532.92  5853.3 1538.42  6287.1 1536.99  6614.8 1540.23
#Mann=9,-1,0
  2059.0    0.05       0  2990.5    0.12       0  3341.6    0.05       0
  4640.7    0.12       0  4822.4    0.05       0  4875.7    0.03       0
  5002.1    0.05       0  5044.2    0.12       0  5155.2    0.05       0
Bank Sta=4875.7,5002.1
Exp/Cntr=0.3,0.1

Type RM Length L Ch R = 1,364845,1792,1792,1792
BEGIN DESCRIPTION:
Mapping XS 30204566
END DESCRIPTION:
XS GIS Cut Line= 3
      1620182.46      6969037.07      1622552.21      6968386.04
      1624140.36      6967761.19
#Sta/Elev= 30
  1231.1 1556.49  1356.4 1547.66  1493.0 1550.09  1588.9 1543.06  1669.3 1553.09
  1679.7 1552.71  1697.3 1546.66  1702.5 1547.68  1710.8 1544.54  1742.1 1542.79
  2112.4 1534.32  2637.3 1526.39  2752.6 1523.59  2799.7 1525.09  2942.4 1521.40
  3323.0 1518.75  4682.9 1521.10  4863.0 1518.85  4924.1 1512.47  4956.6 1511.47
  5086.6 1512.47  5092.0 1514.36  5153.1 1515.62  5170.6 1519.77  5178.2 1524.47
  5200.3 1531.72  5230.1 1534.70  5249.1 1533.95  5350.2 1539.88  5395.3 1541.36
#Mann=7,-1,0
  1231.1    0.05       0  2637.3    0.12       0  2752.6    0.05       0
  4924.1    0.03       0  5086.6    0.05       0  5178.2    0.12       0
  5350.2    0.05       0
Bank Sta=4924.1,5086.6
Exp/Cntr=0.3,0.1

Type RM Length L Ch R = 1,363053,3394,3394,3394
BEGIN DESCRIPTION:
Clear Fork Brazos Rv 93.0
END DESCRIPTION:
XS GIS Cut Line= 4
      1621809.25      6970304.07      1623100.26      6969605.81
      1624255.00      6969538.00      1625255.03      6969538.00
#Sta/Elev= 30
  2375.3 1556.13  2458.7 1559.31  2495.5 1557.73  2575.1 1545.46  2628.0 1529.53
  2671.8 1519.53  2693.7 1518.00  2705.0 1520.41  2715.5 1522.14  2745.6 1518.98
  2924.4 1518.42  3720.3 1516.46  4403.2 1520.84  4539.0 1520.18  4659.2 1514.43
  4789.4 1517.02  4889.6 1514.82  4899.6 1512.46  4942.1 1511.46  5099.8 1512.46
  5109.8 1515.27  5149.8 1514.39  5189.8 1519.18  5299.8 1518.07  5509.8 1524.61
  5549.8 1529.54  5589.8 1523.86  5659.8 1533.54  5719.8 1537.36  5999.8 1543.05
#Mann=5,-1,0
  2375.3    0.05       0  2705.0    0.12       0  2924.4    0.05       0
  4899.6    0.03       0  5099.8    0.05       0
Bank Sta=4899.6,5099.8
Exp/Cntr=0.3,0.1

Type RM Length L Ch R = 1,359659,2732,2732,2732
BEGIN DESCRIPTION:
Mapping XS 9c8e8315
END DESCRIPTION:
XS GIS Cut Line= 3
      1622249.25      6972507.57      1623527.03      6972396.45
      1625784.02      6971070.04
#Sta/Elev= 30
  4240.3 1540.53  4297.2 1541.74  4466.9 1534.64  4523.0 1527.94  4547.2 1536.60
  4567.3 1538.01  4635.9 1529.38  4778.1 1532.74  4828.3 1518.07  4908.6 1512.44
  4931.1 1511.44  5069.2 1512.44  5169.5 1518.32  5451.5 1517.11  5470.7 1513.15
  5495.4 1517.65  5522.9 1525.45  5549.5 1524.71  5565.2 1517.06  5586.6 1514.20
  5704.5 1516.48  5941.0 1517.10  6350.6 1515.45  6433.3 1514.31  6495.1 1513.45
  6791.8 1522.14  7026.2 1521.61  7303.5 1529.04  7793.8 1530.17  8140.8 1540.86
#Mann=9,-1,0
  4240.3    0.05       0  4908.6    0.03       0  5069.2    0.05       0
  5495.4    0.12       0  5704.5    0.05       0  5941.0    0.12       0
  6350.6     0.1       0  6433.3    0.12       0  6495.1    0.05       0
Bank Sta=4908.6,5069.2
Exp/Cntr=0.3,0.1

Type RM Length L Ch R = 1,356927,1460,1460,1460
BEGIN DESCRIPTION:
Mapping XS 866dcaea
END DESCRIPTION:
XS GIS Cut Line= 3
      1625028.33      6974591.46      1625299.59      6973126.64
      1626059.16      6970956.45
#Sta/Elev= 30
  3674.3 1549.70  3736.1 1549.75  3759.2 1553.07  3810.0 1550.55  3871.1 1545.22
  3899.8 1534.89  3952.4 1530.65  4003.3 1540.56  4105.0 1540.63  4126.6 1549.70
  4145.6 1541.56  4202.3 1540.30  4282.4 1539.57  4395.2 1538.11  4440.6 1536.80
  4460.9 1525.99  4507.0 1517.12  4712.8 1513.34  4791.3 1513.35  4867.7 1515.30
  4898.2 1512.33  5026.6 1511.32  5109.1 1512.32  5170.2 1512.92  5434.2 1515.11
  5977.8 1519.59  6179.7 1525.63  6550.5 1527.29  6923.8 1539.94  7463.3 1545.59
#Mann=10,-1,0
  3674.3    0.05       0  4202.3    0.12       0  4282.4    0.05       0
  4395.2    0.12       0  4712.8     0.1       0  4791.3    0.05       0
  4898.2    0.03       0  5109.1    0.05       0  5170.2     0.1       0
  5434.2    0.05       0
Bank Sta=4898.2,5109.1
Exp/Cntr=0.3,0.1

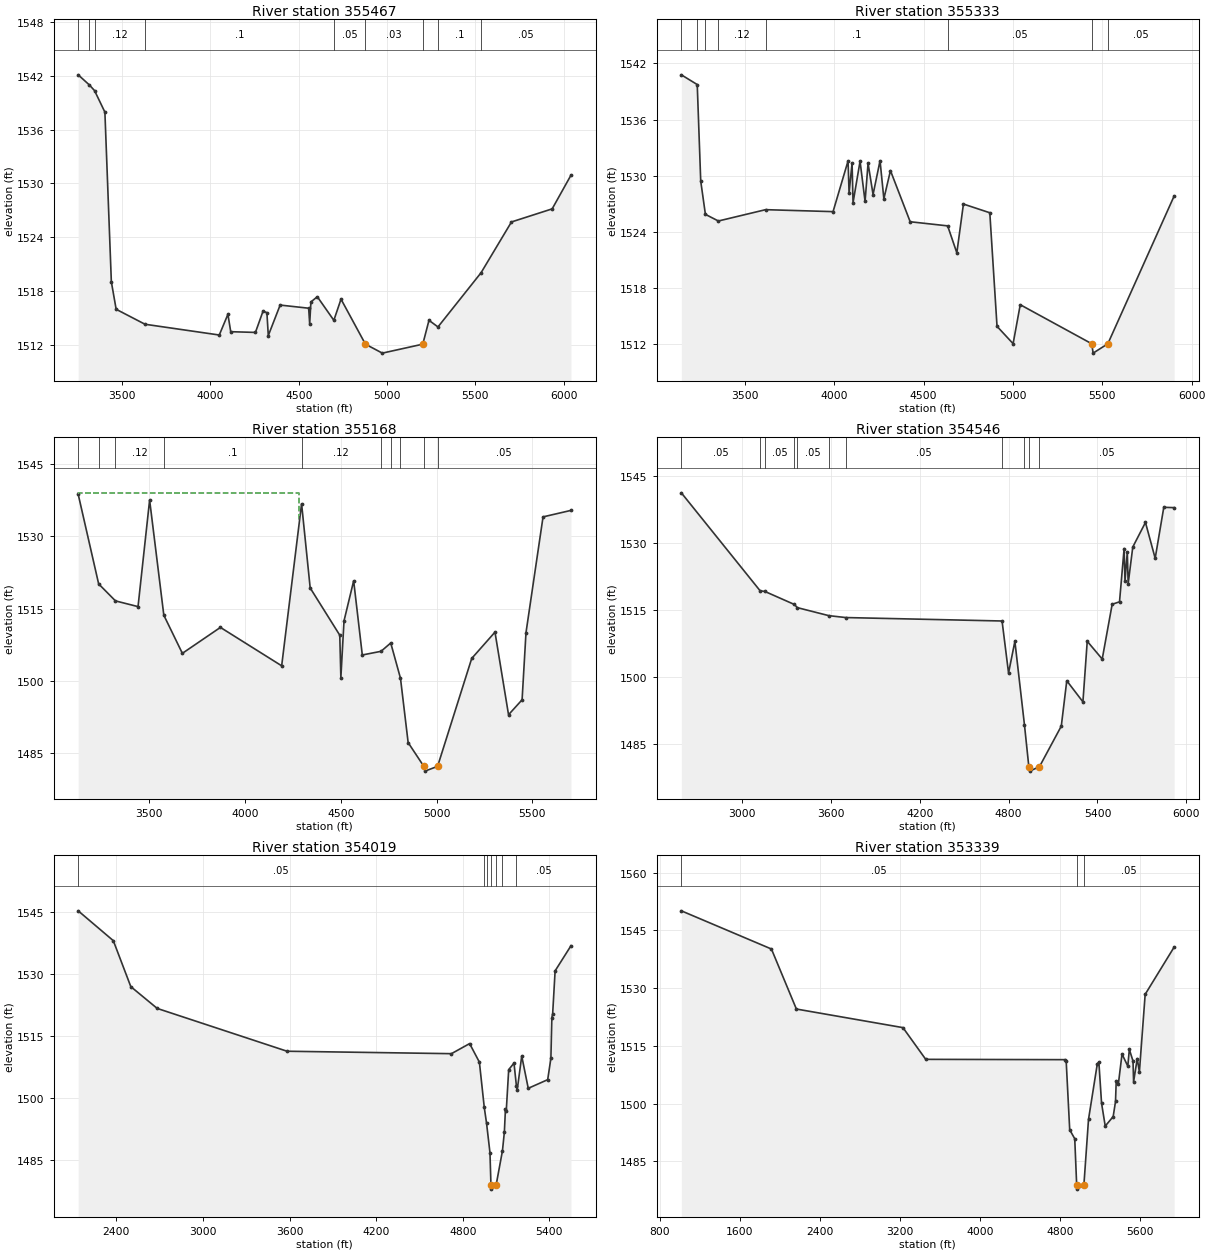
Type RM Length L Ch R = 1,355467,134,134,134
BEGIN DESCRIPTION:
Mapping XS cdde1041
END DESCRIPTION:
XS GIS Cut Line= 6
      1625300.77      6974131.60      1625363.22      6974030.98
      1626618.74      6973292.23      1626691.58      6973170.84
      1626417.58      6972872.57      1626369.12      6972221.74
#Sta/Elev= 30
  3250.9 1542.11  3314.8 1540.97  3343.6 1540.35  3402.2 1537.95  3438.8 1519.02
  3466.0 1515.96  3629.6 1514.29  4050.1 1513.09  4099.1 1515.40  4115.0 1513.46
  4254.9 1513.38  4298.2 1515.76  4319.9 1515.58  4327.8 1513.03  4394.9 1516.43
  4556.5 1516.08  4562.2 1514.34  4569.2 1516.78  4605.5 1517.36  4699.1 1514.73
  4739.7 1517.09  4877.9 1512.07  4973.8 1511.07  5202.9 1512.07  5238.0 1514.73
  5288.9 1513.99  5533.1 1520.04  5705.2 1525.70  5935.8 1527.16  6042.4 1530.92
#Mann=9,-1,0
  3250.9    0.12       0  3314.8    0.05       0  3343.6    0.12       0
  3629.6     0.1       0  4699.1    0.05       0  4877.9    0.03       0
  5202.9    0.05       0  5288.9     0.1       0  5533.1    0.05       0
Bank Sta=4877.9,5202.9
Exp/Cntr=0.3,0.1

Type RM Length L Ch R = 1,355333,165,165,165
BEGIN DESCRIPTION:
Mapping XS 3f5c9455
END DESCRIPTION:
XS GIS Cut Line= 6
      1625356.27      6974141.97      1625491.54      6974030.98
      1626802.57      6973330.38      1626819.91      6973070.26
      1626663.83      6972987.02      1626639.58      6972332.24
#Sta/Elev= 30
  3144.1 1540.78  3233.1 1539.74  3252.6 1529.44  3278.8 1525.88  3351.4 1525.17
  3615.8 1526.38  3993.2 1526.17  4077.2 1531.59  4082.8 1528.15  4099.6 1531.36
  4105.1 1527.13  4144.3 1531.55  4172.3 1527.26  4189.1 1531.33  4217.1 1528.00
  4256.1 1531.61  4277.5 1527.54  4314.4 1530.55  4424.8 1525.09  4634.5 1524.65
  4685.9 1521.77  4722.8 1526.98  4870.4 1526.05  4910.8 1513.92  5000.8 1512.07
  5040.8 1516.23  5441.0 1512.06  5448.5 1511.06  5531.0 1512.06  5902.0 1527.84
#Mann=8,-1,0
  3144.1    0.05       0  3233.1    0.12       0  3278.8    0.05       0
  3351.4    0.12       0  3615.8     0.1       0  4634.5    0.05       0
  5441.0    0.05       0  5531.0    0.05       0
Bank Sta=5441,5531
Exp/Cntr=0.3,0.1

Type RM Length L Ch R = 1,355168,622,622,622
BEGIN DESCRIPTION:
Mapping XS 50a91bc3
END DESCRIPTION:
XS GIS Cut Line= 4
      1625450.37      6974196.34      1626927.42      6973424.03
      1626941.30      6973174.31      1627041.88      6972525.75
#Sta/Elev= 30
  3128.7 1538.77  3235.6 1520.13  3323.4 1516.60  3441.2 1515.41  3501.7 1537.56
  3575.9 1513.62  3672.7 1505.70  3871.4 1511.09  4191.2 1503.11  4295.2 1536.79
  4340.1 1519.29  4494.6 1509.47  4500.3 1500.65  4516.7 1512.44  4567.1 1520.77
  4612.2 1505.36  4710.0 1506.12  4760.7 1507.85  4811.6 1500.52  4851.6 1487.15
  4933.4 1482.22  4939.4 1481.22  5005.4 1482.22  5183.5 1504.64  5305.0 1510.11
  5375.8 1492.94  5446.6 1496.05  5466.9 1509.99  5556.0 1534.06  5701.9 1535.41
#Mann=10,-1,0
  3128.7    0.12       0  3235.6    0.05       0  3323.4    0.12       0
  3575.9     0.1       0  4295.2    0.12       0  4710.0    0.05       0
  4760.7    0.12       0  4811.6    0.05       0  4933.4    0.05       0
  5005.4    0.05       0
#XS Ineff=2,0
    0.00 4283.40 1539.06 5716.60    0.00 1539.06
Permanent Ineff=
       F       F
Bank Sta=4933.4,5005.4
Exp/Cntr=0.3,0.1

Type RM Length L Ch R = 1,354546,527,527,527
BEGIN DESCRIPTION:
Mapping XS 06c9d7c7
END DESCRIPTION:
XS GIS Cut Line= 3
      1625704.66      6974904.76      1626909.08      6974383.93
      1627939.91      6972647.80
#Sta/Elev= 30
  2587.2 1541.25  3119.7 1519.35  3152.5 1519.19  3351.8 1516.28  3371.0 1515.58
  3583.8 1513.79  3698.6 1513.36  4755.3 1512.59  4799.1 1500.96  4841.9 1508.04
  4906.7 1489.36  4936.2 1480.02  4942.2 1479.02  5008.2 1480.02  5155.6 1489.08
  5192.7 1499.23  5301.9 1494.51  5331.0 1508.06  5432.3 1504.08  5499.6 1516.33
  5549.2 1516.88  5580.4 1528.80  5586.3 1521.55  5601.9 1528.05  5607.7 1520.94
  5638.9 1529.13  5724.6 1534.63  5790.3 1526.61  5848.5 1538.01  5918.5 1537.94
#Mann=11,-1,0
  2587.2    0.05       0  3119.7    0.12       0  3152.5    0.05       0
  3351.8    0.12       0  3371.0    0.05       0  3583.8    0.12       0
  3698.6    0.05       0  4755.3    0.12       0  4906.7    0.05       0
  4936.2    0.05       0  5008.2    0.05       0
Bank Sta=4936.2,5008.2
Exp/Cntr=0.3,0.1

Type RM Length L Ch R = 1,354019,680,680,680
BEGIN DESCRIPTION:
Mapping XS 12740f6d
END DESCRIPTION:
XS GIS Cut Line= 4
      1625818.67      6975271.47      1627179.81      6974570.07
      1627638.14      6974215.90      1628207.40      6973042.67
#Sta/Elev= 30
  2135.7 1545.30  2379.1 1538.07  2500.3 1526.94  2683.3 1521.66  3582.8 1511.29
  4721.8 1510.70  4847.8 1513.14  4915.5 1508.65  4949.4 1497.67  4965.3 1493.81
  4988.8 1486.72  4995.6 1478.89  4998.6 1477.89  5031.6 1478.89  5075.3 1487.18
  5088.6 1491.73  5096.1 1497.32  5101.6 1496.80  5118.6 1506.83  5155.3 1508.42
  5172.4 1502.76  5177.5 1501.90  5208.9 1510.12  5254.0 1502.31  5388.7 1504.40
  5410.9 1509.55  5417.6 1519.46  5423.1 1520.31  5440.2 1530.76  5550.2 1536.85
#Mann=7,-1,0
  2135.7    0.05       0  4949.4    0.12       0  4965.3    0.05       0
  4995.6    0.05       0  5031.6    0.05       0  5075.3    0.12       0
  5172.4    0.05       0
Bank Sta=4995.6,5031.6
Exp/Cntr=0.3,0.1

Type RM Length L Ch R = 1,353339,484,484,484
BEGIN DESCRIPTION:
Mapping XS 0f442376
END DESCRIPTION:
XS GIS Cut Line= 5
      1625277.87      6975839.32      1627209.31      6975166.57
      1627719.30      6974884.45      1628142.47      6974504.68
      1629053.95      6973028.95
#Sta/Elev= 30
  1013.1 1550.06  1914.7 1540.14  2164.3 1524.55  3230.8 1519.72  3458.7 1511.48
  4855.1 1511.40  4864.1 1510.97  4899.3 1493.18  4949.7 1490.86  4969.1 1478.77
  4975.1 1477.77  5041.1 1478.77  5087.4 1495.87  5175.6 1510.33  5191.0 1510.75
  5218.1 1500.06  5254.8 1494.15  5334.2 1496.61  5357.7 1500.54  5364.7 1505.89
  5386.0 1505.03  5422.7 1512.85  5480.6 1509.72  5496.0 1514.06  5532.7 1511.04
  5538.5 1505.66  5575.2 1511.68  5596.5 1508.20  5654.4 1528.37  5944.3 1540.64
#Mann=3,-1,0
  1013.1    0.05       0  4969.1    0.03       0  5041.1    0.05       0
Bank Sta=4969.1,5041.1
Exp/Cntr=0.3,0.1

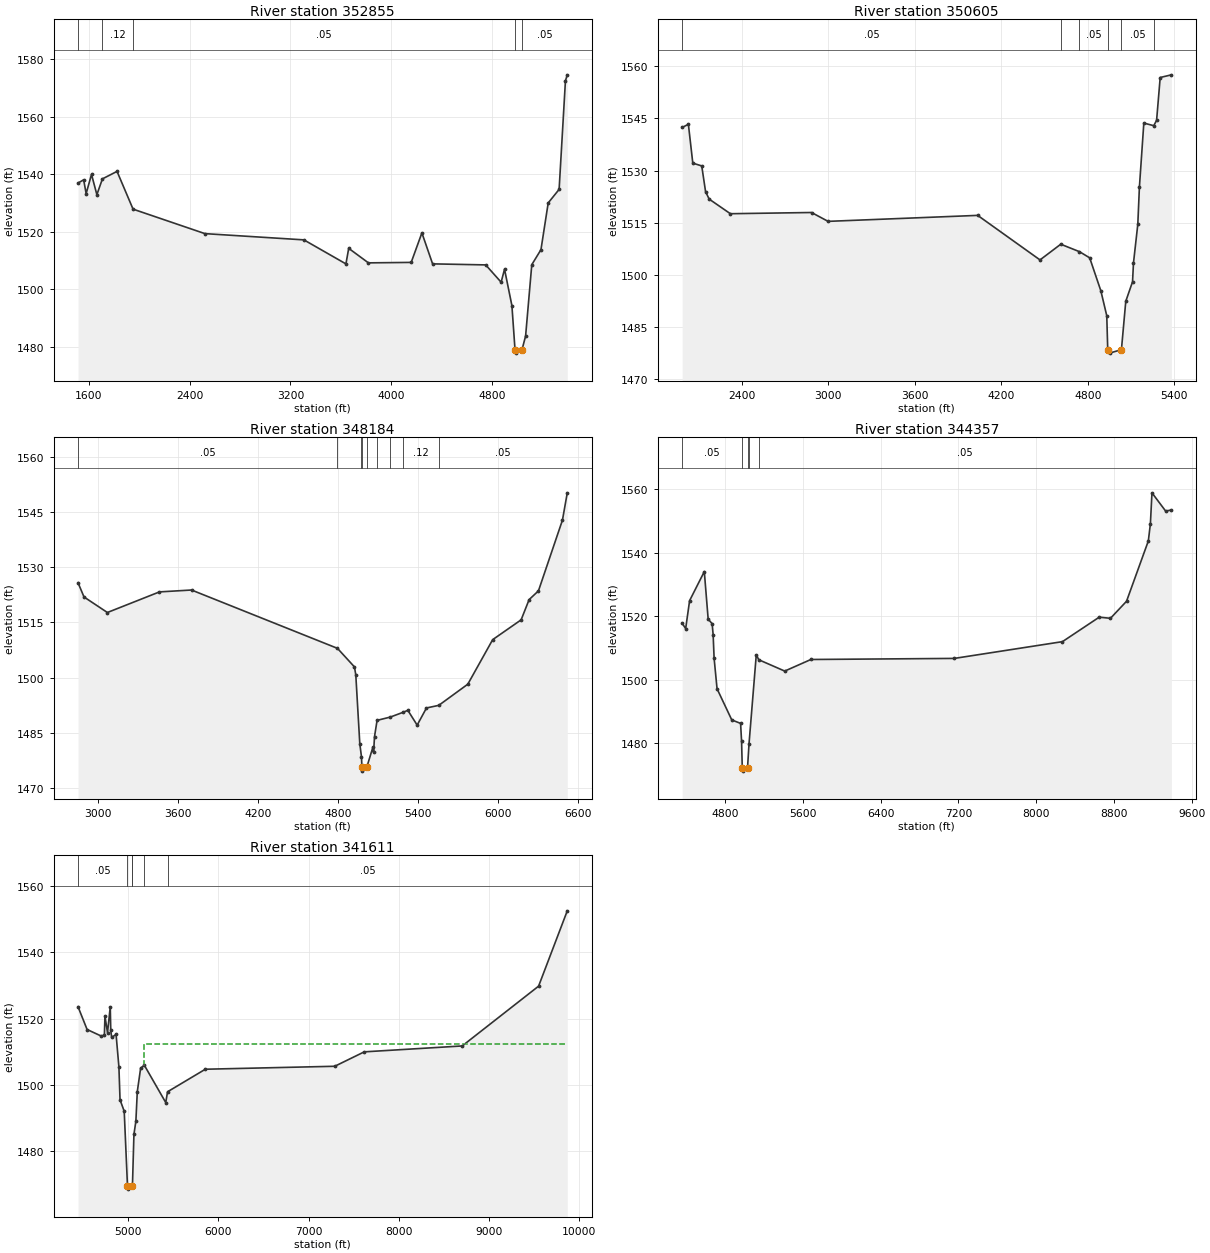
Type RM Length L Ch R = 1,352855,2250,2250,2250
BEGIN DESCRIPTION:
Mapping XS 498caced
END DESCRIPTION:
XS GIS Cut Line= 5
      1626124.27      6975936.96      1627708.45      6975361.88
      1628283.53      6974884.45      1628706.71      6974450.42
      1629184.15      6973755.97
#Sta/Elev= 30
  1514.7 1536.95  1559.5 1538.06  1579.3 1533.28  1621.9 1539.95  1664.4 1532.90
  1708.5 1538.40  1824.3 1541.00  1951.5 1527.86  2521.8 1519.34  3306.9 1517.17
  3640.3 1508.81  3662.4 1514.22  3818.7 1509.17  4158.1 1509.33  4243.0 1519.60
  4327.9 1508.82  4749.2 1508.46  4871.6 1502.44  4898.6 1506.95  4957.1 1494.30
  4982.1 1478.76  4986.6 1477.76  5036.1 1478.76  5065.8 1483.71  5114.8 1508.53
  5187.6 1513.76  5245.1 1530.03  5331.7 1534.74  5381.8 1572.51  5396.4 1574.60
#Mann=5,-1,0
  1514.7    0.05       0  1708.5    0.12       0  1951.5    0.05       0
  4982.1    0.03       0  5036.1    0.05       0
Bank Sta=4982.1,5036.1
Exp/Cntr=0.3,0.1

Type RM Length L Ch R = 1,350605,2421,2421,2421
BEGIN DESCRIPTION:
Mapping XS ff54809c
END DESCRIPTION:
XS GIS Cut Line= 2
      1626872.93      6976761.63      1630170.73      6975958.87
#Sta/Elev= 30
  1985.9 1542.42  2029.2 1543.33  2059.8 1532.15  2121.8 1531.35  2148.4 1523.94
  2173.3 1521.80  2320.4 1517.59  2883.4 1517.94  2998.3 1515.39  4036.1 1517.11
  4468.4 1504.29  4612.4 1508.81  4742.3 1506.66  4813.0 1504.89  4890.4 1495.41
  4931.5 1488.22  4938.2 1478.46  4943.2 1478.46  4950.7 1477.46  5033.2 1478.46
  5063.4 1492.39  5110.3 1498.00  5116.8 1503.40  5146.8 1514.53  5158.0 1525.29
  5188.6 1543.69  5257.3 1542.93  5277.2 1544.46  5302.1 1556.80  5380.0 1557.57
#Mann=6,-1,0
  1985.9    0.05       0  4612.4   0.075       0  4742.3    0.05       0
  4943.2    0.05       0  5033.2    0.05       0  5257.3    0.05       0
Bank Sta=4943.2,5033.2
Exp/Cntr=0.3,0.1

Type RM Length L Ch R = 1,348184,3827,3827,3827
BEGIN DESCRIPTION:
Mapping XS 144c3aa3
END DESCRIPTION:
XS GIS Cut Line= 3
      1627155.05      6978009.45      1629368.60      6978183.06
      1630821.30      6978118.02
#Sta/Elev= 30
  2847.3 1525.78  2892.5 1521.90  3067.9 1517.69  3459.1 1523.28  3699.9 1523.79
  4795.9 1507.97  4923.6 1502.93  4933.6 1500.74  4963.7 1482.05  4976.3 1478.53
  4979.5 1475.67  4982.5 1474.67  5015.5 1475.67  5062.9 1481.27  5067.2 1479.75
  5074.1 1484.02  5093.4 1488.44  5192.6 1489.33  5286.3 1490.59  5324.3 1491.16
  5394.4 1487.15  5464.4 1491.80  5556.7 1492.51  5774.8 1498.25  5961.6 1510.33
  6175.2 1515.70  6235.2 1521.19  6305.3 1523.56  6485.5 1542.74  6521.8 1550.15
#Mann=9,-1,0
  2847.3    0.05       0  4795.9    0.12       0  4976.3    0.05       0
  4979.5    0.05       0  5015.5    0.05       0  5093.4    0.12       0
  5192.6     0.1       0  5286.3    0.12       0  5556.7    0.05       0
Bank Sta=4979.5,5015.5
Exp/Cntr=0.3,0.1

Type RM Length L Ch R = 1,344357,2746,2746,2746
BEGIN DESCRIPTION:
Mapping XS 956fea84
END DESCRIPTION:
XS GIS Cut Line= 4
      1629119.03      6981449.12      1631549.59      6981123.60
      1632667.21      6980136.19      1633050.28      6979115.61
#Sta/Elev= 30
  4357.5 1517.81  4393.8 1516.15  4434.2 1524.94  4585.5 1534.10  4625.2 1519.11
  4666.2 1517.69  4676.3 1514.24  4686.4 1506.77  4716.7 1497.19  4868.0 1487.38
  4958.8 1486.28  4968.9 1480.65  4976.1 1472.25  4980.6 1471.25  5030.1 1472.25
  5045.5 1479.84  5120.2 1507.89  5145.8 1506.33  5412.8 1502.76  5682.2 1506.41
  7157.6 1506.75  8270.2 1512.03  8648.4 1519.74  8764.1 1519.38  8929.4 1524.75
  9153.7 1543.74  9175.0 1549.18  9191.1 1558.90  9331.7 1553.16  9391.2 1553.49
#Mann=5,-1,0
  4357.5    0.05       0  4976.1    0.05       0  5030.1    0.05       0
  5045.5    0.12       0  5145.8    0.05       0
Bank Sta=4976.1,5030.1
Exp/Cntr=0.3,0.1

Type RM Length L Ch R = 1,341611,1999,1999,1999
BEGIN DESCRIPTION:
Mapping XS 44f365a5
END DESCRIPTION:
XS GIS Cut Line= 3
      1630659.84      6984020.72      1632840.83      6980266.40
      1633383.00      6979333.10
#Sta/Elev= 30
  4444.5 1523.60  4545.2 1516.72  4700.0 1514.77  4736.8 1514.97  4743.0 1520.73
  4771.5 1515.78  4801.8 1523.55  4807.5 1516.44  4817.5 1514.31  4866.3 1515.25
  4897.8 1505.40  4910.2 1495.52  4956.5 1492.07  4992.7 1469.58  4996.5 1468.58
  5037.7 1469.58  5047.7 1469.59  5064.2 1485.11  5085.7 1489.05  5101.4 1497.98
  5138.7 1505.10  5180.1 1505.91  5416.8 1494.69  5436.7 1497.94  5855.5 1504.74
  7289.2 1505.63  7616.4 1509.98  8701.4 1511.76  9547.8 1529.79  9865.7 1552.51
#Mann=6,-1,0
  4444.5    0.05       0  4992.7    0.05       0  5037.7    0.05       0
  5047.7     0.1       0  5180.1    0.12       0  5436.7    0.05       0
#XS Ineff=2,0
       0                 5173.60    0.00 1512.43
Permanent Ineff=
       F       F
Bank Sta=4992.7,5037.7
Exp/Cntr=0.3,0.1