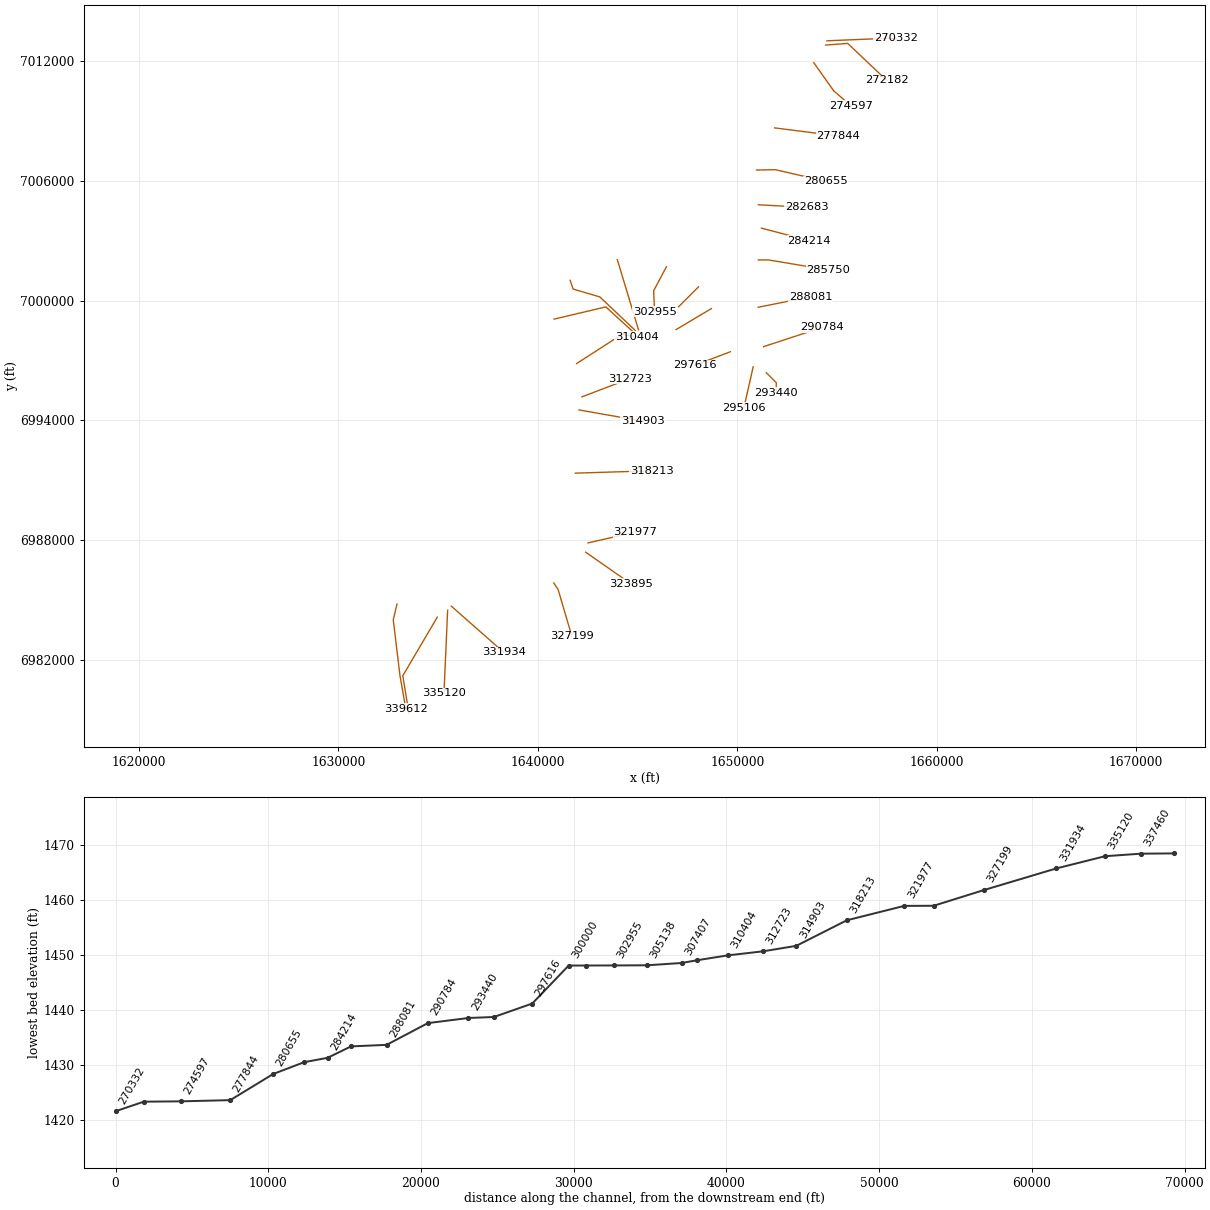
HEC-RAS study Clear Fork Brazos Rv.prj: Clear Fork Brazos Rv Base Level Engineering

--- Clear Fork Brazos Rv.g01 (geometry) --- (continued)

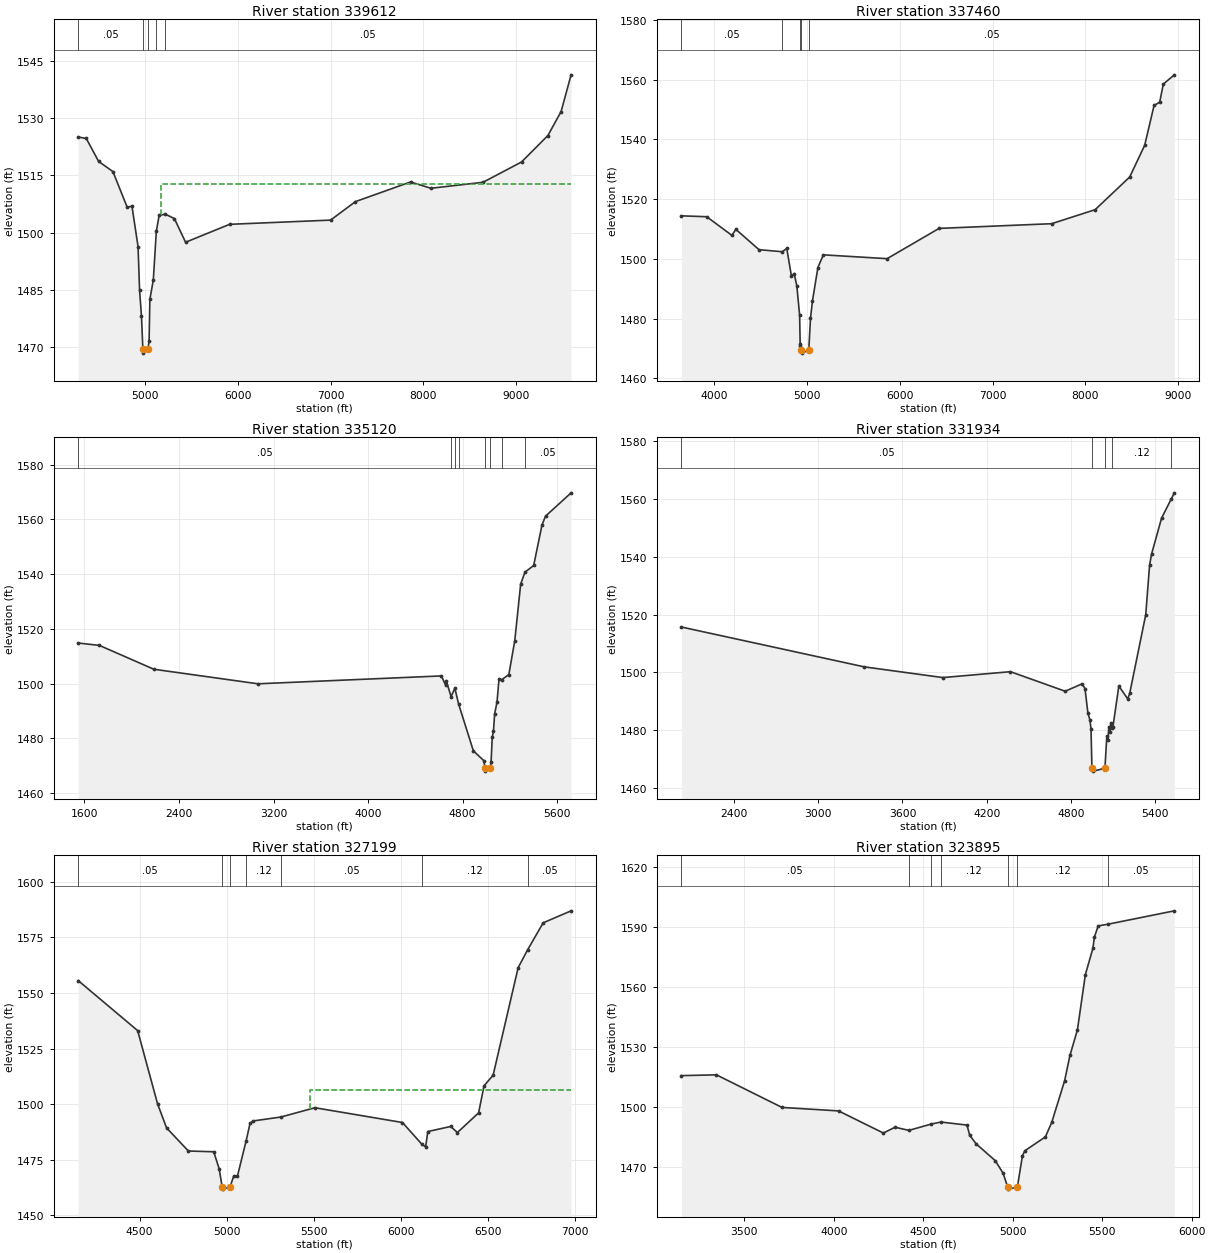
Type RM Length L Ch R = 1,339612,2152,2152,2152
BEGIN DESCRIPTION:
Mapping XS 8e5bb11e
END DESCRIPTION:
XS GIS Cut Line= 4
      1632937.22      6984792.91      1632752.25      6984003.68
      1633085.22      6981228.90      1633380.87      6979541.20
#Sta/Elev= 30
  4274.9 1525.04  4362.1 1524.65  4495.6 1518.65  4649.7 1515.99  4803.8 1506.66
  4855.1 1506.93  4921.0 1496.35  4937.3 1484.95  4957.8 1478.21  4973.0 1469.51
  4977.5 1468.51  5027.0 1469.51  5040.0 1471.65  5048.3 1482.56  5085.5 1487.63
  5117.9 1500.34  5148.6 1504.56  5216.2 1504.84  5312.8 1503.70  5433.7 1497.51
  5909.0 1502.20  6998.5 1503.30  7266.7 1508.14  7861.0 1513.28  8080.4 1511.63
  8642.5 1513.19  9058.8 1518.50  9343.0 1525.42  9485.2 1531.67  9593.6 1541.30
#Mann=5,-1,0
  4274.9    0.05       0  4973.0    0.05       0  5027.0    0.05       0
  5117.9    0.12       0  5216.2    0.05       0
#XS Ineff=2,0
       0                 5164.40    0.00 1512.80
Permanent Ineff=
       F       F
Bank Sta=4973,5027
Exp/Cntr=0.3,0.1

Type RM Length L Ch R = 1,337460,2340,2340,2340
BEGIN DESCRIPTION:
Mapping XS 866e5e92
END DESCRIPTION:
XS GIS Cut Line= 3
      1634956.69      6984140.06      1633229.49      6981205.89
      1633538.69      6979321.98
#Sta/Elev= 30
  3644.4 1514.40  3916.7 1514.11  4188.1 1507.87  4231.0 1509.88  4481.0 1503.07
  4732.7 1502.39  4779.7 1503.50  4830.4 1494.16  4859.7 1495.07  4888.4 1490.90
  4918.3 1481.13  4924.1 1471.44  4927.1 1470.84  4936.1 1469.46  4942.9 1468.46
  5017.1 1469.46  5035.5 1480.08  5056.9 1485.97  5115.5 1497.11  5174.1 1501.35
  5861.4 1500.07  6421.6 1510.20  7634.8 1511.77  8104.0 1516.46  8476.7 1527.40
  8638.1 1538.00  8739.4 1551.33  8800.2 1552.46  8839.3 1558.50  8958.3 1561.59
#Mann=5,-1,0
  3644.4    0.05       0  4732.7    0.12       0  4927.1    0.05       0
  4936.1    0.03       0  5017.1    0.05       0
Bank Sta=4936.1,5017.1
Exp/Cntr=0.3,0.1

Type RM Length L Ch R = 1,335120,3186,3186,3186
BEGIN DESCRIPTION:
Mapping XS ea6ca10d
END DESCRIPTION:
XS GIS Cut Line= 2
      1635477.54      6984487.32      1635293.13      6980321.80
#Sta/Elev= 30
  1547.6 1514.81  1727.1 1513.94  2187.5 1505.23  3068.4 1499.91  4619.9 1502.79
  4656.2 1499.36  4661.2 1500.98  4701.9 1495.25  4733.7 1498.29  4766.2 1492.42
  4890.2 1475.43  4980.3 1471.76  4987.7 1469.00  4991.4 1468.00  5032.7 1469.00
  5040.3 1471.43  5050.3 1480.41  5060.4 1482.62  5070.4 1488.93  5090.4 1493.18
  5107.6 1501.78  5129.4 1501.39  5190.5 1503.26  5240.5 1515.61  5290.6 1536.32
  5326.9 1540.70  5400.7 1543.14  5470.8 1557.92  5500.8 1561.17  5717.2 1569.69
#Mann=8,-1,0
  1547.6    0.05       0  4701.9    0.12       0  4733.7    0.05       0
  4766.2    0.12       0  4987.7    0.07       0  5032.7    0.12       0
  5129.4    0.12       0  5326.9    0.05       0
Bank Sta=4987.7,5032.7
Exp/Cntr=0.3,0.1

Type RM Length L Ch R = 1,331934,4735,4735,4735
BEGIN DESCRIPTION:
Mapping XS 62725a57
END DESCRIPTION:
XS GIS Cut Line= 2
      1635662.03      6984693.46      1638297.82      6982372.23
#Sta/Elev= 30
  2025.2 1515.70  3327.7 1501.90  3887.5 1498.19  4369.4 1500.23  4759.3 1493.46
  4879.8 1496.02  4900.7 1494.36  4921.6 1485.76  4935.8 1483.56  4943.4 1480.44
  4950.1 1466.78  4952.6 1466.78  4960.1 1465.78  5042.6 1466.78  5056.3 1478.03
  5063.9 1476.41  5070.6 1481.19  5078.1 1479.41  5084.8 1482.38  5092.1 1480.62
  5099.0 1480.93  5141.7 1495.25  5205.3 1490.79  5219.5 1492.81  5333.3 1519.94
  5360.9 1537.15  5375.1 1541.02  5446.2 1553.41  5516.2 1560.17  5537.4 1562.19
#Mann=5,-1,0
  2025.2    0.05       0  4952.6    0.03       0  5042.6    0.05       0
  5092.1    0.12       0  5516.2    0.05       0
Bank Sta=4952.6,5042.6
Exp/Cntr=0.3,0.1

Type RM Length L Ch R = 1,327199,3304,3304,3304
BEGIN DESCRIPTION:
Clear Fork Brazos Rv 84.0
END DESCRIPTION:
XS GIS Cut Line= 3
      1640797.68      6985854.78      1641014.69      6985533.60
      1641705.00      6983187.99
#Sta/Elev= 30
  4147.6 1555.60  4489.4 1533.10  4603.6 1500.22  4655.4 1489.39  4780.8 1478.99
  4926.7 1478.64  4958.0 1470.89  4975.0 1462.85  4978.7 1461.85  5020.0 1462.85
  5041.4 1467.66  5062.3 1467.56  5112.6 1483.51  5135.2 1491.42  5153.5 1492.50
  5313.4 1494.28  5507.8 1498.44  6011.1 1491.80  6123.0 1482.00  6144.5 1480.89
  6156.8 1487.73  6288.3 1490.02  6326.9 1487.30  6448.7 1496.13  6479.9 1508.29
  6532.1 1513.05  6676.0 1561.39  6730.3 1569.42  6819.8 1581.56  6980.3 1586.95
#Mann=7,-1,0
  4147.6    0.05       0  4975.0    0.05       0  5020.0    0.05       0
  5112.6    0.12       0  5313.4    0.05       0  6123.0    0.12       0
  6730.3    0.05       0
#XS Ineff=2,0
       0                 5480.90    0.00 1506.61
Permanent Ineff=
       F       F
Bank Sta=4975,5020
Exp/Cntr=0.3,0.1

Type RM Length L Ch R = 1,323895,1918,1918,1918
BEGIN DESCRIPTION:
Mapping XS b8737ab3
END DESCRIPTION:
XS GIS Cut Line= 2
      1642400.30      6987395.30      1644660.28      6985820.23
#Sta/Elev= 30
  3148.7 1515.72  3344.2 1516.11  3710.7 1499.82  4026.6 1498.08  4277.0 1487.03
  4342.4 1489.91  4420.1 1488.36  4544.6 1491.51  4598.7 1492.52  4744.7 1490.99
  4759.5 1485.93  4795.3 1481.65  4902.6 1473.19  4946.2 1466.94  4971.9 1459.98
  4976.4 1458.98  5025.9 1459.98  5054.4 1475.71  5068.1 1478.18  5182.7 1485.10
  5218.5 1492.46  5290.0 1513.13  5319.7 1525.79  5361.6 1538.60  5406.1 1566.24
  5447.9 1579.29  5456.7 1585.03  5477.6 1590.56  5533.1 1591.43  5903.4 1598.10
#Mann=7,-1,0
  3148.7    0.05       0  4420.1    0.12       0  4544.6    0.05       0
  4598.7    0.12       0  4971.9    0.07       0  5025.9    0.12       0
  5533.1    0.05       0
Bank Sta=4971.9,5025.9
Exp/Cntr=0.3,0.1

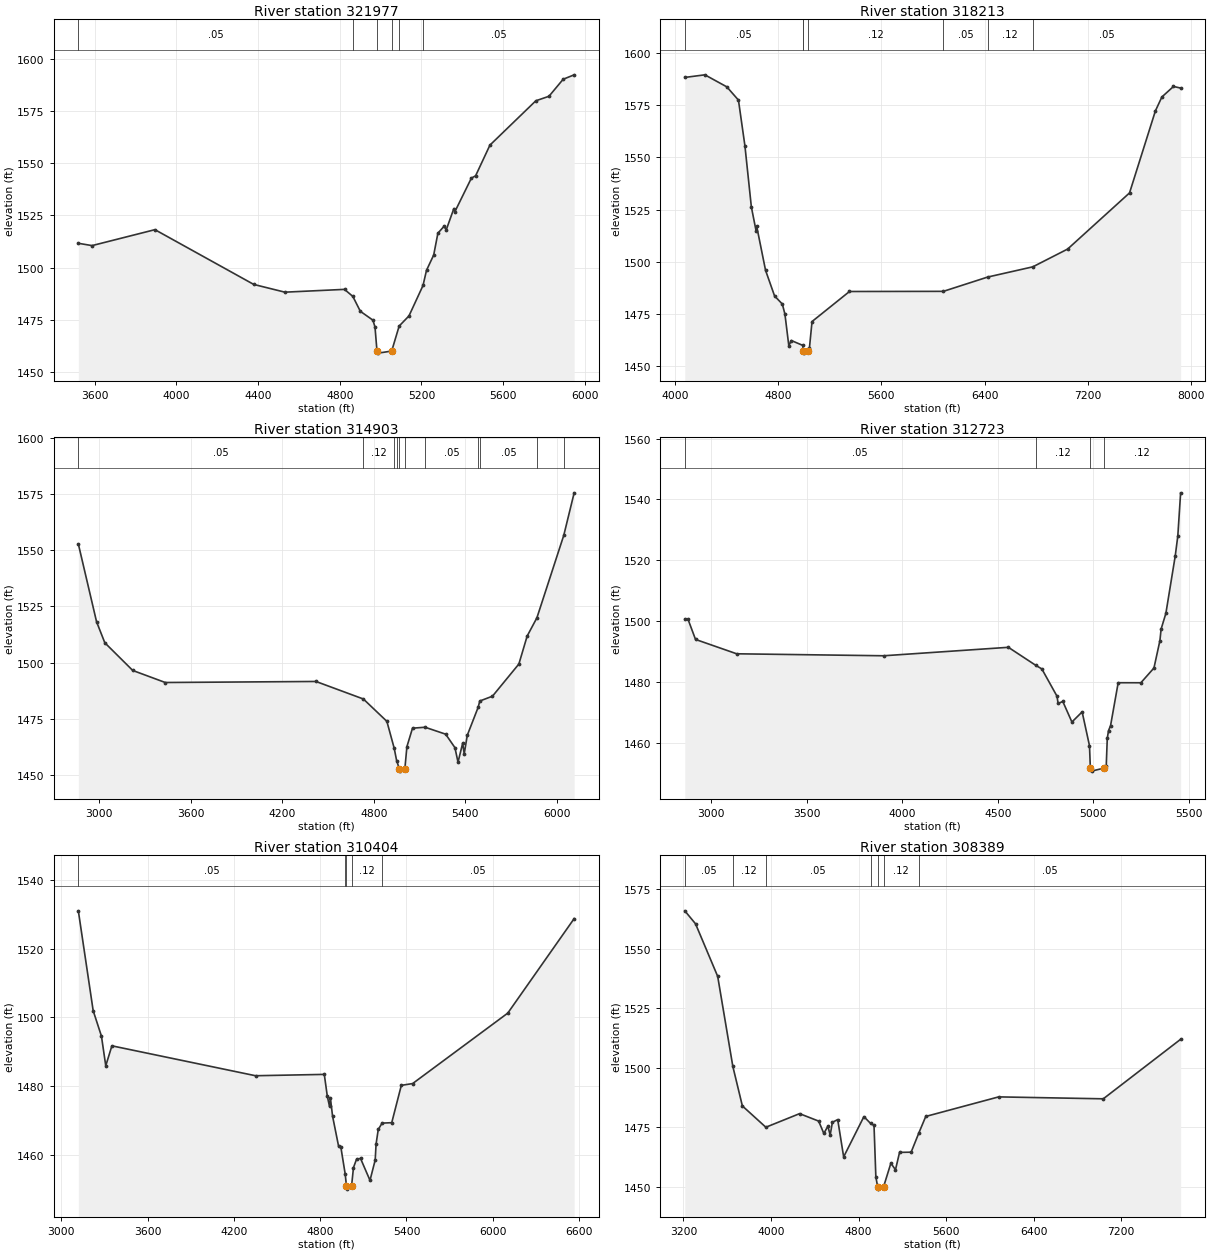
Type RM Length L Ch R = 1,321977,3764,3764,3764
BEGIN DESCRIPTION:
Mapping XS 1de1d8a1
END DESCRIPTION:
XS GIS Cut Line= 2
      1642519.61      6987861.87      1644885.09      6988404.41
#Sta/Elev= 30
  3520.5 1511.63  3587.6 1510.52  3895.4 1518.16  4379.1 1491.90  4531.5 1488.19
  4823.3 1489.53  4864.2 1486.15  4900.8 1479.02  4962.4 1474.77  4972.6 1471.47
  4982.3 1459.96  4988.3 1458.96  5054.3 1459.96  5090.8 1471.94  5138.9 1476.81
  5207.6 1491.39  5224.7 1498.68  5259.9 1506.00  5280.4 1516.46  5310.5 1519.78
  5321.5 1518.13  5358.5 1528.28  5363.6 1526.79  5444.2 1542.85  5465.1 1544.01
  5535.1 1558.70  5759.8 1579.96  5824.2 1582.13  5893.6 1590.29  5947.4 1592.41
#Mann=6,-1,0
  3520.5    0.05       0  4864.2     0.1       0  4982.3    0.07       0
  5054.3     0.1       0  5090.8    0.12       0  5207.6    0.05       0
Bank Sta=4982.3,5054.3
Exp/Cntr=0.3,0.1

Type RM Length L Ch R = 1,318213,3310,3310,3310
BEGIN DESCRIPTION:
Mapping XS 5729e91d
END DESCRIPTION:
XS GIS Cut Line= 2
      1641879.42      6991355.80      1645720.27      6991475.15
#Sta/Elev= 30
  4076.9 1588.30  4232.6 1589.55  4402.6 1583.79  4492.7 1577.45  4542.7 1555.66
  4592.7 1526.34  4629.1 1514.95  4634.1 1517.03  4702.8 1495.97  4772.8 1483.68
  4832.8 1479.83  4852.9 1475.01  4882.9 1459.93  4902.9 1462.36  4991.7 1460.03
  4995.2 1457.34  4998.2 1456.34  5031.2 1457.34  5042.9 1458.81  5063.0 1471.46
  5353.1 1485.84  6080.8 1485.91  6424.7 1492.76  6773.8 1497.64  7043.9 1506.15
  7523.7 1533.03  7724.2 1572.30  7774.3 1578.95  7864.3 1583.98  7919.6 1583.21
#Mann=7,-1,0
  4076.9    0.05       0  4991.7    0.12       0  4995.2    0.07       0
  5031.2    0.12       0  6080.8    0.05       0  6424.7    0.12       0
  6773.8    0.05       0
Bank Sta=4995.2,5031.2
Exp/Cntr=0.3,0.1

Type RM Length L Ch R = 1,314903,2180,2180,2180
BEGIN DESCRIPTION:
Mapping XS 17d3d0be
END DESCRIPTION:
XS GIS Cut Line= 3
      1642063.89      6994524.21      1643224.94      6994318.05
      1645264.84      6993959.98
#Sta/Elev= 30
  2863.3 1552.74  2982.9 1518.10  3036.9 1508.79  3219.9 1496.47  3433.2 1491.11
  4421.0 1491.57  4731.9 1483.77  4885.9 1473.83  4934.0 1461.85  4949.8 1456.37
  4967.8 1452.69  4970.8 1451.69  5003.8 1452.69  5017.2 1462.57  5053.9 1470.79
  5136.2 1471.21  5271.1 1468.13  5332.0 1462.13  5352.3 1455.66  5382.8 1464.13
  5392.9 1459.42  5413.2 1467.67  5484.1 1480.05  5495.0 1482.88  5578.1 1485.02
  5751.2 1499.33  5805.5 1511.77  5869.5 1519.90  6045.7 1556.61  6113.6 1575.48
#Mann=11,-1,0
  2863.3    0.05       0  4731.9    0.12       0  4934.0    0.05       0
  4949.8    0.12       0  4967.8    0.07       0  5003.8    0.12       0
  5136.2    0.05       0  5484.1    0.12       0  5495.0    0.05       0
  5869.5    0.12       0  6045.7    0.05       0
Bank Sta=4967.8,5003.8
Exp/Cntr=0.3,0.1

Type RM Length L Ch R = 1,312723,2319,2319,2319
BEGIN DESCRIPTION:
Clear Fork Brazos Rv 80.0
END DESCRIPTION:
XS GIS Cut Line= 3
      1642212.62      6995177.71      1644205.00      6995938.00
      1644641.54      6996088.60
#Sta/Elev= 30
  2862.4 1500.73  2879.1 1500.62  2918.5 1493.98  3133.8 1489.26  3903.2 1488.61
  4555.4 1491.39  4698.7 1485.47  4730.6 1484.28  4810.1 1475.29  4815.5 1472.92
  4840.2 1473.59  4887.9 1466.83  4941.4 1470.16  4979.9 1459.03  4984.4 1451.69
  4990.4 1450.69  5056.4 1451.69  5067.6 1452.52  5072.9 1461.45  5079.5 1464.02
  5090.1 1465.64  5130.0 1479.75  5248.8 1479.74  5317.2 1484.59  5348.4 1493.61
  5354.6 1497.38  5379.6 1502.57  5428.6 1521.44  5442.0 1528.01  5456.7 1542.17
#Mann=4,-1,0
  2862.4    0.05       0  4698.7    0.12       0  4984.4    0.07       0
  5056.4    0.12       0
Bank Sta=4984.4,5056.4
Exp/Cntr=0.3,0.1

Type RM Length L Ch R = 1,310404,2015,2015,2015
BEGIN DESCRIPTION:
Mapping XS 676dc003
END DESCRIPTION:
XS GIS Cut Line= 3
      1641944.58      6996846.27      1644223.20      6998311.10
      1644950.09      6998180.91
#Sta/Elev= 30
  3118.5 1530.99  3221.7 1501.91  3279.2 1494.50  3309.2 1485.87  3351.8 1491.68
  4350.4 1482.97  4828.6 1483.36  4849.7 1476.95  4864.9 1474.04  4870.9 1476.55
  4886.1 1471.20  4928.3 1462.38  4943.5 1462.24  4973.8 1454.38  4982.5 1450.95
  4985.5 1449.95  5018.5 1450.95  5031.4 1456.21  5052.5 1458.62  5080.5 1458.89
  5146.3 1452.50  5182.6 1458.44  5188.5 1463.03  5203.7 1467.32  5230.5 1469.17
  5297.5 1469.30  5364.2 1480.17  5442.8 1480.69  6104.4 1501.21  6565.8 1528.73
#Mann=5,-1,0
  3118.5    0.05       0  4973.8    0.12       0  4982.5    0.07       0
  5018.5    0.12       0  5230.5    0.05       0
Bank Sta=4982.5,5018.5
Exp/Cntr=0.3,0.1

Type RM Length L Ch R = 1,308389,982,982,982
BEGIN DESCRIPTION:
Mapping XS c0a6bf55
END DESCRIPTION:
XS GIS Cut Line= 3
      1640812.59      6999070.86      1643407.79      6999684.78
      1644784.47      6998429.02
#Sta/Elev= 30
  3212.1 1565.94  3310.2 1560.49  3512.6 1538.41  3651.1 1500.57  3738.1 1484.00
  3952.7 1475.05  4260.8 1480.76  4435.0 1477.63  4482.4 1472.45  4519.5 1475.49
  4540.2 1471.76  4560.7 1477.13  4609.2 1478.26  4663.5 1462.61  4848.5 1479.51
  4909.3 1476.66  4940.9 1475.85  4957.7 1454.19  4974.2 1450.06  4978.7 1449.06
  5028.2 1450.06  5095.1 1459.95  5137.0 1457.18  5174.2 1464.49  5280.1 1464.58
  5351.3 1472.74  5413.6 1479.58  6079.7 1487.80  7035.7 1486.99  7742.3 1511.99
#Mann=7,-1,0
  3212.1    0.05       0  3651.1    0.12       0  3952.7    0.05       0
  4909.3    0.12       0  4974.2    0.07       0  5028.2    0.12       0
  5351.3    0.05       0
Bank Sta=4974.2,5028.2
Exp/Cntr=0.3,0.1

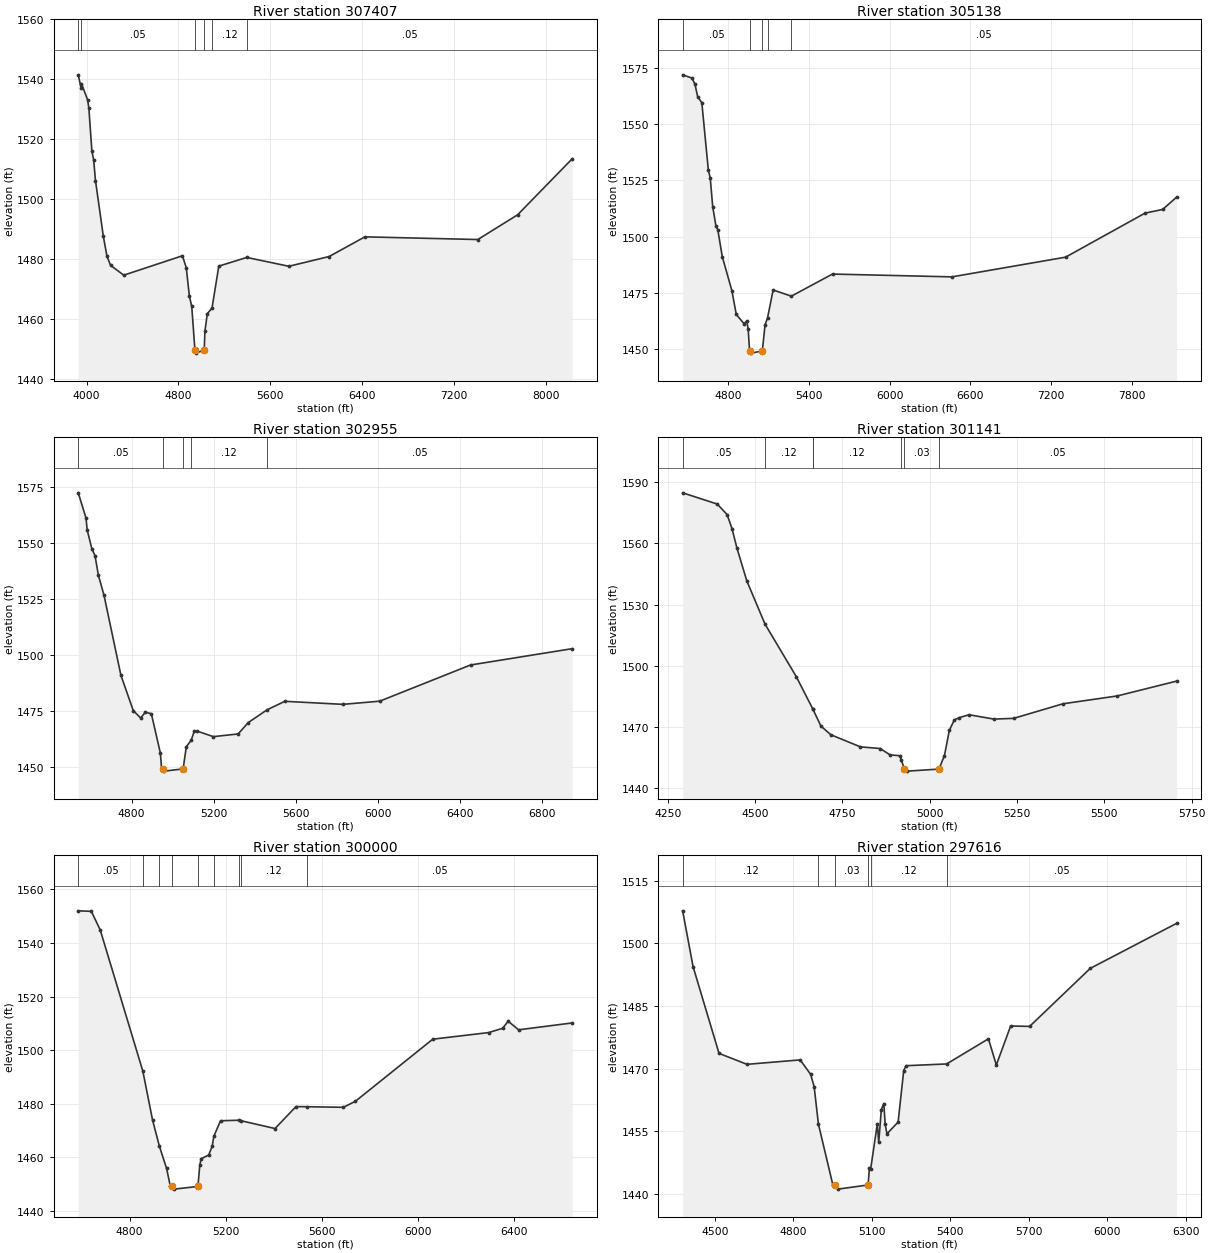
Type RM Length L Ch R = 1,307407,2269,2269,2269
BEGIN DESCRIPTION:
Mapping XS d23fb629
END DESCRIPTION:
XS GIS Cut Line= 4
      1641621.83      7001014.97      1641769.90      7000577.01
      1643106.70      7000186.38      1644885.13      6998506.38
#Sta/Elev= 30
  3927.5 1541.50  3951.9 1537.18  3955.6 1538.58  4008.8 1533.17  4020.0 1530.38
  4046.2 1516.10  4061.5 1513.18  4077.6 1506.20  4146.0 1487.57  4177.7 1480.89
  4209.3 1477.88  4323.9 1474.60  4834.9 1481.08  4868.4 1477.06  4895.2 1467.63
  4916.0 1464.14  4943.7 1449.57  4950.4 1448.57  5024.7 1449.57  5030.6 1455.85
  5051.5 1461.73  5092.4 1463.59  5151.6 1477.62  5395.2 1480.52  5762.0 1477.57
  6112.5 1480.83  6424.0 1487.40  7407.1 1486.50  7753.8 1494.76  8229.0 1513.46
#Mann=6,-1,0
  3927.5    0.12       0  3955.6    0.05       0  4943.7    0.05       0
  5024.7    0.05       0  5092.4    0.12       0  5395.2    0.05       0
Bank Sta=4943.7,5024.7
Exp/Cntr=0.3,0.1

Type RM Length L Ch R = 1,305138,2183,2183,2183
BEGIN DESCRIPTION:
Mapping XS 0c69a64c
END DESCRIPTION:
XS GIS Cut Line= 2
      1643984.50      7002054.57      1645047.86      6998538.97
#Sta/Elev= 30
  4459.7 1571.90  4529.2 1570.45  4551.6 1567.67  4571.0 1562.26  4602.4 1559.49
  4650.4 1529.77  4665.1 1525.91  4683.3 1513.27  4706.9 1504.82  4721.5 1502.89
  4754.5 1491.00  4825.6 1475.99  4858.5 1465.35  4915.8 1461.26  4936.7 1462.49
  4947.1 1458.67  4957.3 1449.15  4962.3 1449.15  4969.8 1448.15  5052.3 1449.15
  5072.5 1460.73  5091.1 1463.82  5132.5 1476.23  5267.8 1473.47  5574.0 1483.31
  6462.0 1482.06  7307.0 1490.82  7898.4 1510.42  8029.1 1512.04  8132.6 1517.51
#Mann=5,-1,0
  4459.7    0.05       0  4962.3    0.03       0  5052.3    0.05       0
  5091.1    0.12       0  5267.8    0.05       0
Bank Sta=4962.3,5052.3
Exp/Cntr=0.3,0.1

Type RM Length L Ch R = 1,302955,1814,1814,1814
BEGIN DESCRIPTION:
Mapping XS 477dd2df
END DESCRIPTION:
XS GIS Cut Line= 3
      1646447.59      7001696.51      1645807.41      7000492.09
      1645850.76      6999451.69
#Sta/Elev= 30
  4540.5 1572.28  4578.2 1561.08  4584.1 1555.69  4606.8 1547.34  4622.2 1544.25
  4638.5 1535.58  4666.1 1526.52  4748.4 1490.83  4808.7 1475.08  4844.6 1471.83
  4867.2 1474.42  4896.6 1473.72  4940.5 1456.13  4946.5 1449.12  4952.2 1449.12
  4960.4 1448.12  5051.2 1449.12  5066.7 1458.99  5090.5 1461.87  5105.0 1465.81
  5116.4 1466.07  5198.6 1463.50  5319.1 1464.71  5368.8 1469.80  5459.9 1475.47
  5546.7 1479.27  5829.6 1477.91  6008.7 1479.33  6450.7 1495.47  6945.8 1502.75
#Mann=5,-1,0
  4540.5    0.05       0  4952.2    0.03       0  5051.2    0.05       0
  5090.5    0.12       0  5459.9    0.05       0
Bank Sta=4952.2,5051.2
Exp/Cntr=0.3,0.1

Type RM Length L Ch R = 1,301141,1141,1141,1141
BEGIN DESCRIPTION:
Clear Fork Brazos Rv 77.0
END DESCRIPTION:
XS GIS Cut Line= 3
      1648054.97      7000687.97      1647555.00      7000188.00
      1647054.98      6999687.98
#Sta/Elev= 30
  4292.7 1584.90  4391.7 1579.39  4419.9 1574.24  4434.1 1567.27  4448.2 1557.71
  4476.5 1541.58  4528.6 1520.36  4617.9 1494.60  4664.8 1478.86  4664.9 1478.82
  4688.6 1470.26  4716.9 1466.00  4801.8 1460.03  4858.3 1459.23  4886.6 1456.08
  4914.9 1455.68  4919.2 1453.44  4927.5 1449.11  4935.8 1448.11  5026.5 1449.11
  5042.2 1455.71  5056.3 1468.17  5070.5 1473.26  5084.6 1474.41  5112.9 1475.82
  5183.6 1473.69  5240.2 1474.04  5381.6 1481.21  5537.2 1485.07  5706.9 1492.35
#Mann=7,-1,0
  4292.7    0.05       0  4528.6    0.12       0  4664.8    0.05       0
  4664.9    0.12       0  4919.2    0.05       0  4927.5    0.03       0
  5026.5    0.05       0
Bank Sta=4927.5,5026.5
Exp/Cntr=0.3,0.1

Type RM Length L Ch R = 1,300000,2384,2384,2384
BEGIN DESCRIPTION:
Mapping XS 53526ef3
END DESCRIPTION:
XS GIS Cut Line= 2
      1648704.52      6999602.32      1646935.90      6998549.83
#Sta/Elev= 30
  4586.4 1552.01  4641.0 1551.83  4678.0 1544.86  4855.6 1492.14  4896.1 1473.89
  4924.7 1464.07  4954.5 1455.81  4969.9 1449.28  4977.1 1449.10  4986.1 1448.10
  5085.1 1449.10  5092.8 1457.02  5098.6 1459.46  5129.8 1460.81  5144.4 1464.05
  5151.5 1467.87  5179.3 1473.62  5256.4 1473.83  5264.9 1473.64  5406.3 1470.72
  5493.5 1478.92  5538.1 1478.87  5691.3 1478.65  5741.2 1480.90  6063.7 1504.09
  6296.4 1506.55  6354.6 1508.15  6377.9 1510.80  6420.9 1507.58  6644.5 1510.15
#Mann=9,-1,0
  4586.4    0.05       0  4855.6    0.12       0  4924.7    0.05       0
  4977.1    0.03       0  5085.1    0.05       0  5151.5    0.12       0
  5256.4    0.05       0  5264.9    0.12       0  5538.1    0.05       0
Bank Sta=4977.1,5085.1
Exp/Cntr=0.3,0.1

Type RM Length L Ch R = 1,297616,2510,2510,2510
BEGIN DESCRIPTION:
Clear Fork Brazos Rv 76.0
END DESCRIPTION:
XS GIS Cut Line= 2
      1649655.01      6997438.01      1647889.80      6996766.29
#Sta/Elev= 30
  4376.9 1507.80  4416.7 1494.46  4516.0 1473.68  4623.0 1471.06  4826.3 1472.12
  4866.4 1468.66  4879.8 1465.68  4896.0 1456.76  4951.3 1442.19  4960.0 1442.19
  4970.5 1441.19  5086.0 1442.19  5091.2 1446.25  5095.9 1446.03  5121.3 1456.86
  5126.6 1452.36  5136.6 1460.24  5146.0 1461.66  5151.4 1456.72  5158.0 1454.42
  5200.8 1457.24  5222.2 1469.55  5231.0 1470.73  5386.3 1471.15  5546.2 1477.17
  5576.3 1470.90  5631.1 1480.24  5703.7 1480.14  5935.6 1494.03  6265.6 1504.80
#Mann=6,-1,0
  4376.9    0.12       0  4896.0    0.05       0  4960.0    0.03       0
  5086.0    0.05       0  5095.9    0.12       0  5386.3    0.05       0
Bank Sta=4960,5086
Exp/Cntr=0.3,0.1

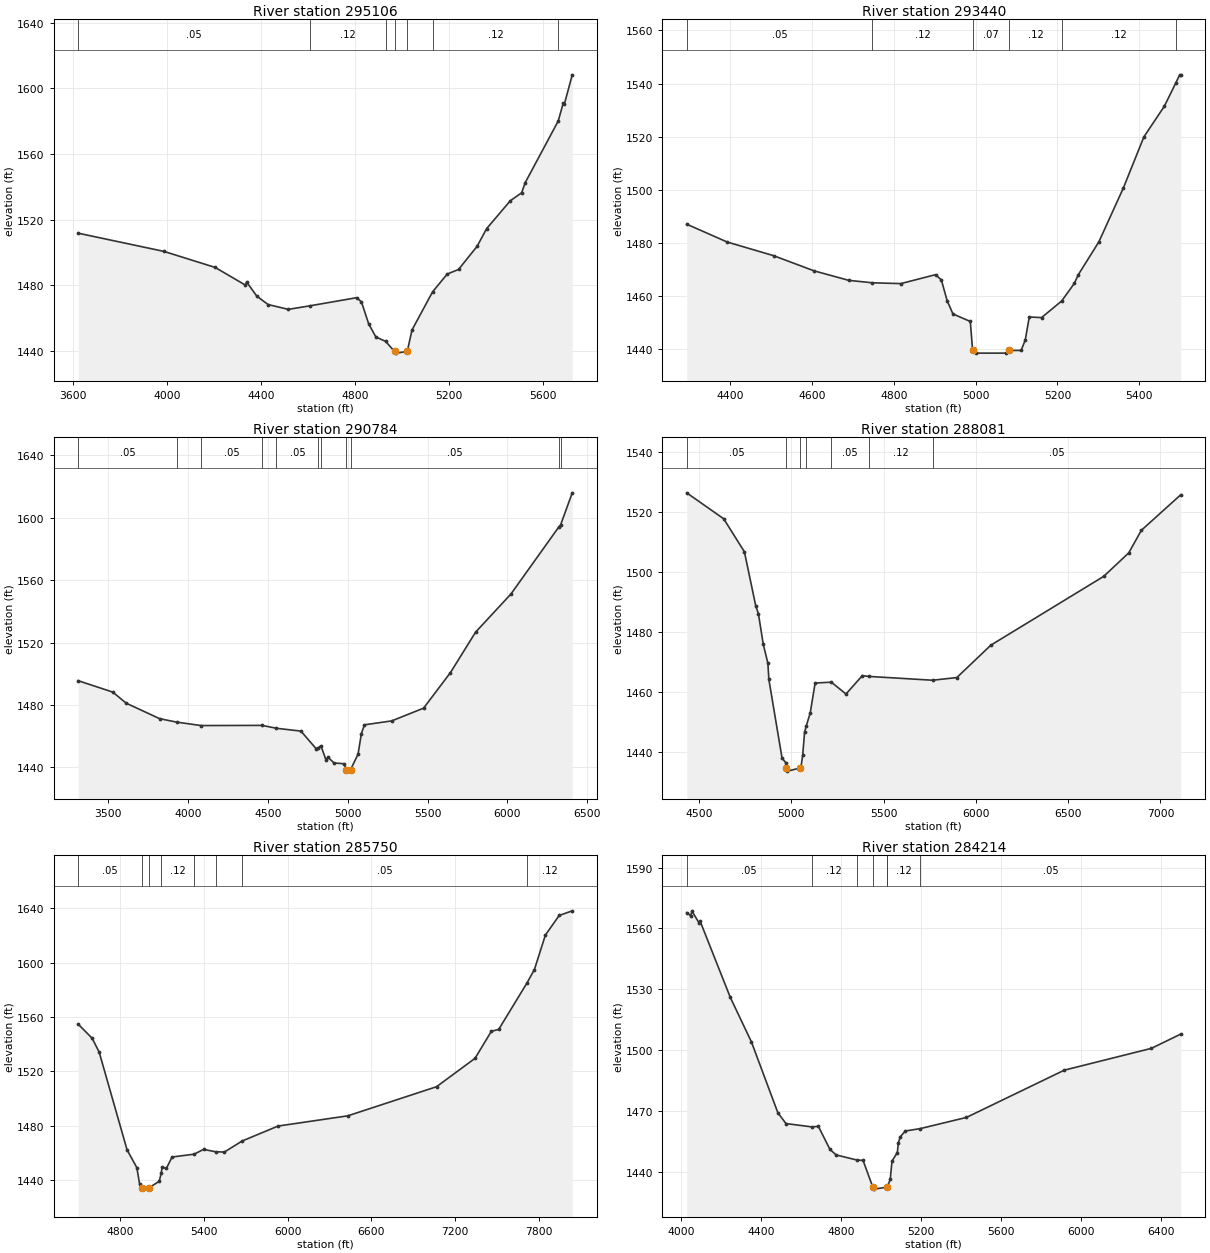
Type RM Length L Ch R = 1,295106,1666,1666,1666
BEGIN DESCRIPTION:
Mapping XS bf588705
END DESCRIPTION:
XS GIS Cut Line= 2
      1650798.72      6996683.46      1650332.18      6994632.86
#Sta/Elev= 30
  3621.6 1511.82  3986.1 1500.74  4204.2 1490.98  4333.4 1480.18  4338.5 1482.08
  4381.5 1473.49  4429.7 1468.35  4515.8 1465.41  4606.4 1467.53  4806.6 1472.52
  4827.1 1470.00  4857.9 1456.62  4888.6 1448.56  4930.1 1445.92  4968.1 1439.74
  4972.6 1438.74  5022.1 1439.74  5042.5 1452.89  5130.0 1476.09  5192.3 1486.92
  5240.5 1489.73  5319.4 1503.81  5360.4 1514.67  5460.9 1531.59  5509.1 1536.46
  5524.5 1542.69  5665.1 1580.25  5686.4 1591.25  5691.5 1590.74  5724.6 1608.33
#Mann=7,-1,0
  3621.6    0.05       0  4606.4    0.12       0  4930.1    0.05       0
  4968.1    0.05       0  5022.1    0.05       0  5130.0    0.12       0
  5665.1    0.05       0
Bank Sta=4968.1,5022.1
Exp/Cntr=0.3,0.1

Type RM Length L Ch R = 1,293440,2656,2656,2656
BEGIN DESCRIPTION:
Clear Fork Brazos Rv 75.0
END DESCRIPTION:
XS GIS Cut Line= 3
      1651454.99      6996388.01      1651955.00      6995888.00
      1651955.00      6995388.02
#Sta/Elev= 30
  4294.2 1487.09  4393.2 1480.37  4506.3 1475.25  4605.3 1469.53  4690.2 1465.95
  4748.1 1465.03  4817.5 1464.73  4902.3 1468.09  4916.5 1466.11  4930.6 1458.27
  4944.8 1453.30  4987.2 1450.48  4992.8 1439.56  5000.3 1438.56  5075.3 1438.56
  5082.8 1439.56  5111.3 1439.58  5121.3 1443.40  5131.3 1452.16  5161.3 1451.93
  5210.5 1458.19  5241.3 1464.79  5251.3 1468.13  5301.3 1480.44  5361.3 1500.76
  5411.3 1519.94  5461.3 1531.48  5488.9 1540.12  5498.8 1543.30  5501.3 1543.30
#Mann=6,-1,0
  4294.2    0.05       0  4748.1    0.12       0  4992.8    0.07       0
  5082.8    0.12       0  5210.5    0.12       0  5488.9    0.05       0
Bank Sta=4992.8,5082.8
Exp/Cntr=0.3,0.1

Type RM Length L Ch R = 1,290784,2703,2703,2703
BEGIN DESCRIPTION:
Mapping XS b72f16ef
END DESCRIPTION:
XS GIS Cut Line= 2
      1651319.54      6997692.61      1654260.03      6998658.30
#Sta/Elev= 30
  3311.6 1495.53  3527.9 1488.25  3612.1 1481.15  3821.5 1471.23  3928.6 1469.01
  4081.4 1466.82  4463.6 1466.92  4552.5 1465.09  4706.7 1463.26  4801.4 1452.07
  4816.7 1452.72  4832.1 1453.81  4864.6 1444.50  4875.1 1446.65  4913.6 1442.87
  4977.3 1442.36  4990.8 1438.63  4993.0 1437.63  5017.8 1438.63  5064.6 1448.48
  5085.6 1461.71  5104.5 1467.29  5275.1 1469.79  5475.1 1477.96  5643.5 1500.74
  5801.4 1526.70  6022.4 1551.06  6323.3 1594.13  6333.0 1595.20  6406.6 1615.87
#Mann=11,-1,0
  3311.6    0.05       0  3928.6    0.12       0  4081.4    0.05       0
  4463.6    0.12       0  4552.5    0.05       0  4816.7    0.12       0
  4832.1    0.05       0  4990.8    0.05       0  5017.8    0.05       0
  6323.3    0.12       0  6333.0    0.05       0
Bank Sta=4990.8,5017.8
Exp/Cntr=0.3,0.1

Type RM Length L Ch R = 1,288081,2331,2331,2331
BEGIN DESCRIPTION:
Mapping XS 7b2b0c0f
END DESCRIPTION:
XS GIS Cut Line= 2
      1651048.26      6999667.43      1653674.11      7000188.26
#Sta/Elev= 30
  4432.6 1526.44  4633.2 1517.78  4745.3 1506.78  4806.5 1488.84  4821.4 1486.08
  4847.3 1476.00  4872.6 1469.62  4877.8 1464.25  4949.2 1438.05  4969.6 1436.46
  4972.3 1434.67  4978.3 1433.67  5044.3 1434.67  5051.2 1434.67  5061.4 1439.15
  5071.5 1446.72  5080.0 1448.63  5102.1 1453.08  5128.5 1463.04  5216.5 1463.32
  5295.8 1459.38  5384.4 1465.50  5419.4 1465.24  5764.8 1463.97  5896.3 1464.86
  6080.8 1475.66  6692.5 1498.60  6827.9 1506.42  6896.4 1513.95  7109.6 1525.79
#Mann=7,-1,0
  4432.6    0.05       0  4972.3    0.05       0  5044.3    0.05       0
  5080.0    0.12       0  5216.5    0.05       0  5419.4    0.12       0
  5764.8    0.05       0
Bank Sta=4972.3,5044.3
Exp/Cntr=0.3,0.1

Type RM Length L Ch R = 1,285750,1536,1536,1536
BEGIN DESCRIPTION:
Clear Fork Brazos Rv 73.0
END DESCRIPTION:
XS GIS Cut Line= 3
      1651054.95      7002038.00      1651555.00      7002038.00
      1654554.97      7001538.00
#Sta/Elev= 30
  4499.1 1554.73  4599.1 1544.35  4649.1 1534.19  4849.1 1462.29  4919.1 1449.18
  4939.1 1437.06  4953.0 1434.39  4957.5 1433.39  5007.0 1434.39  5080.2 1439.21
  5093.9 1445.33  5100.5 1449.48  5130.9 1448.63  5171.5 1457.02  5330.2 1459.11
  5397.1 1462.63  5483.4 1460.90  5546.6 1460.66  5673.9 1468.79  5931.8 1479.80
  6431.1 1487.31  7067.3 1508.73  7343.5 1529.62  7460.1 1549.44  7513.4 1550.94
  7715.8 1585.03  7769.3 1594.98  7847.9 1620.32  7946.8 1634.75  8040.5 1638.15
#Mann=8,-1,0
  4499.1    0.05       0  4953.0    0.05       0  5007.0    0.05       0
  5093.9    0.12       0  5330.2    0.05       0  5483.4    0.12       0
  5673.9    0.05       0  7715.8    0.12       0
Bank Sta=4953,5007
Exp/Cntr=0.3,0.1

Type RM Length L Ch R = 1,284214,1531,1531,1531
BEGIN DESCRIPTION:
Mapping XS b1c2323f
END DESCRIPTION:
XS GIS Cut Line= 2
      1651211.99      7003628.76      1653601.32      7003005.86
#Sta/Elev= 30
  4029.2 1567.82  4049.9 1566.26  4055.1 1568.71  4090.4 1562.78  4095.6 1563.77
  4247.2 1525.95  4352.7 1504.00  4485.0 1468.99  4525.4 1463.68  4654.8 1462.03
  4687.4 1462.31  4745.4 1450.88  4776.4 1448.18  4878.5 1445.72  4910.7 1445.48
  4959.5 1432.31  4965.5 1431.31  5031.5 1432.31  5032.4 1432.43  5046.6 1436.14
  5055.4 1445.16  5082.0 1449.36  5087.1 1454.10  5096.7 1457.17  5122.4 1460.01
  5196.5 1461.19  5427.4 1466.71  5916.7 1490.05  6351.8 1500.81  6498.4 1507.85
#Mann=7,-1,0
  4029.2    0.05       0  4654.8    0.12       0  4878.5    0.05       0
  4959.5    0.05       0  5031.5    0.05       0  5032.4    0.12       0
  5196.5    0.05       0
Bank Sta=4959.5,5031.5
Exp/Cntr=0.3,0.1

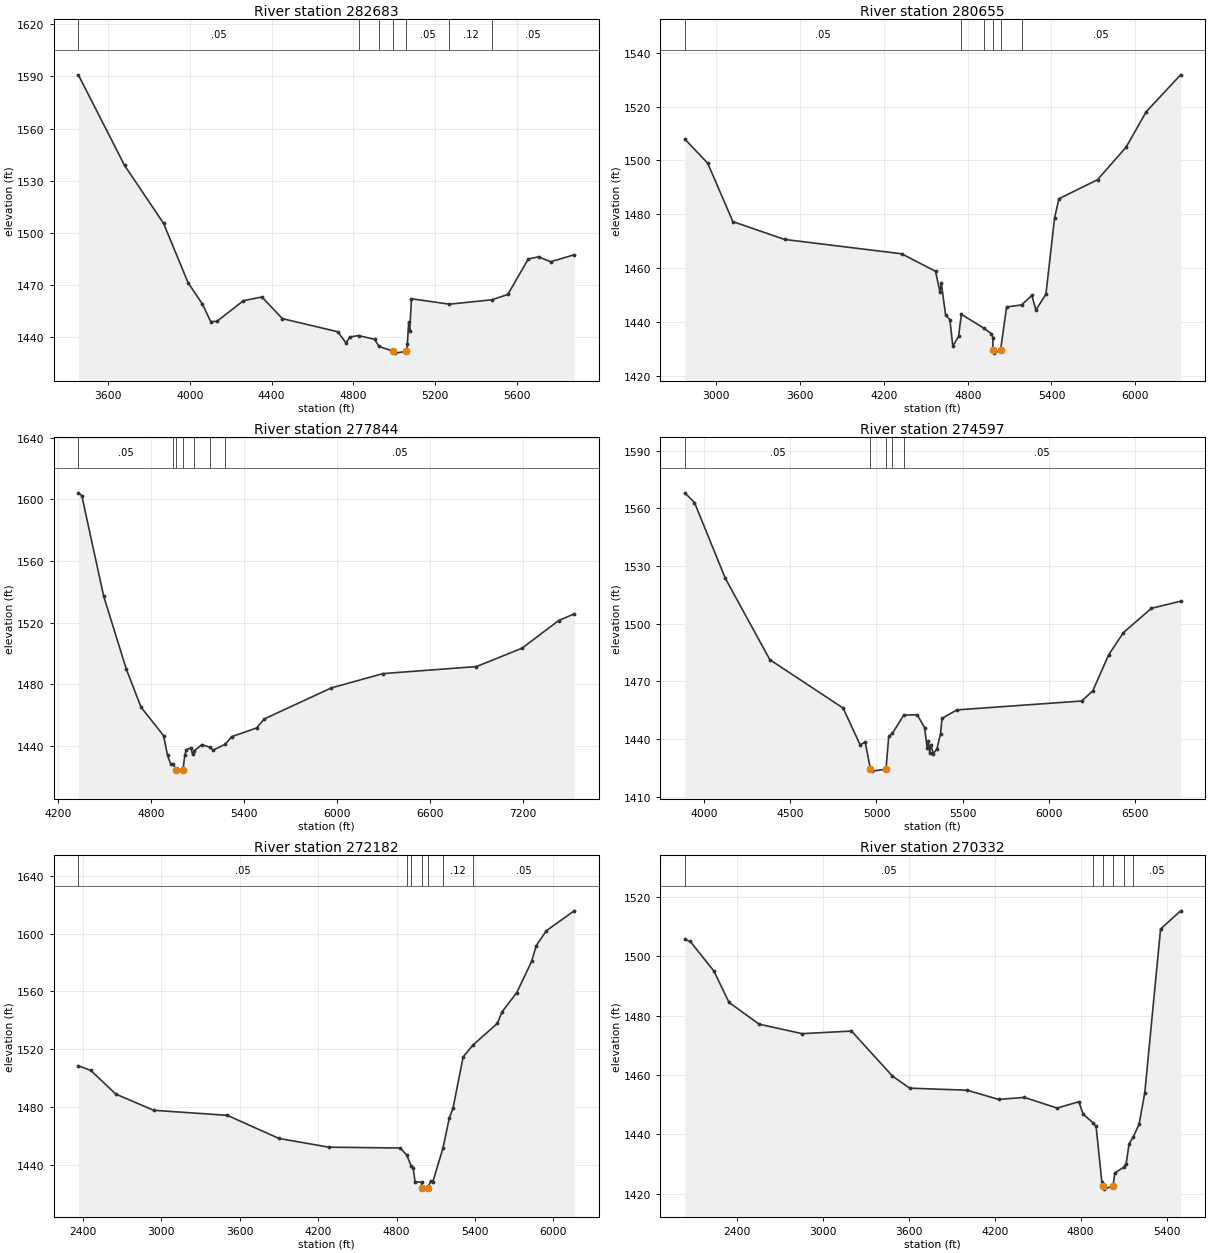
Type RM Length L Ch R = 1,282683,2028,2028,2028
BEGIN DESCRIPTION:
Mapping XS b9bf7f8e
END DESCRIPTION:
XS GIS Cut Line= 2
      1651059.14      7004799.82      1653478.84      7004669.61
#Sta/Elev= 30
  3455.5 1590.94  3681.7 1538.68  3872.0 1505.34  3992.1 1471.07  4062.2 1458.74
  4102.3 1448.73  4132.3 1448.81  4262.5 1460.76  4352.7 1462.87  4452.8 1450.41
  4723.2 1442.84  4763.3 1436.48  4783.3 1439.86  4825.0 1440.64  4903.5 1438.47
  4924.3 1434.44  4995.6 1431.52  5000.8 1430.52  5058.6 1431.52  5063.7 1435.88
  5069.9 1448.34  5074.9 1443.49  5083.7 1461.86  5269.0 1458.74  5475.2 1461.24
  5554.4 1464.32  5654.5 1484.81  5704.6 1486.02  5764.7 1483.19  5878.7 1487.23
#Mann=7,-1,0
  3455.5    0.05       0  4825.0    0.12       0  4924.3    0.05       0
  4995.6    0.05       0  5058.6    0.05       0  5269.0    0.12       0
  5475.2    0.05       0
Bank Sta=4995.6,5058.6
Exp/Cntr=0.3,0.1

Type RM Length L Ch R = 1,280655,2811,2811,2811
BEGIN DESCRIPTION:
Mapping XS ae6b22d2
END DESCRIPTION:
XS GIS Cut Line= 3
      1650960.89      7006540.22      1651916.35      7006557.63
      1654444.52      7005971.70
#Sta/Elev= 30
  2774.0 1507.96  2938.1 1498.99  3118.2 1477.27  3488.2 1470.65  4327.3 1465.30
  4570.0 1458.80  4600.8 1451.19  4611.0 1454.36  4641.8 1442.51  4672.6 1440.80
  4693.1 1431.01  4734.2 1434.57  4754.7 1442.79  4913.2 1437.73  4970.3 1435.56
  4980.6 1434.15  4980.9 1429.37  4985.4 1428.37  5034.9 1429.37  5078.5 1445.54
  5185.4 1446.29  5259.4 1449.81  5288.5 1444.38  5360.4 1450.34  5422.0 1478.56
  5452.8 1485.77  5729.9 1492.85  5935.2 1505.02  6078.9 1518.17  6324.8 1531.85
#Mann=6,-1,0
  2774.0    0.05       0  4754.7    0.12       0  4913.2    0.05       0
  4980.9    0.07       0  5034.9    0.05       0  5185.4    0.05       0
Bank Sta=4980.9,5034.9
Exp/Cntr=0.3,0.1

Type RM Length L Ch R = 1,277844,3247,3247,3247
BEGIN DESCRIPTION:
Mapping XS 60efb378
END DESCRIPTION:
XS GIS Cut Line= 2
      1651872.96      7008651.81      1655051.12      7008250.47
#Sta/Elev= 30
  4329.5 1604.13  4351.7 1602.35  4492.8 1537.26  4639.1 1489.89  4734.7 1465.08
  4879.8 1446.69  4906.1 1433.82  4926.2 1428.05  4944.0 1427.93  4960.8 1424.61
  4964.6 1423.61  5005.8 1424.61  5017.0 1433.79  5027.0 1437.49  5057.3 1438.60
  5067.4 1434.41  5079.7 1436.88  5127.8 1440.83  5179.9 1439.08  5200.7 1437.19
  5280.1 1441.13  5319.3 1445.95  5480.6 1451.56  5531.0 1457.48  5964.4 1477.59
  6297.0 1486.86  6901.8 1491.43  7196.3 1503.36  7431.9 1521.23  7532.9 1525.61
#Mann=7,-1,0
  4329.5    0.05       0  4944.0    0.12       0  4960.8    0.07       0
  5005.8    0.12       0  5079.7    0.05       0  5179.9    0.12       0
  5280.1    0.05       0
Bank Sta=4960.8,5005.8
Exp/Cntr=0.3,0.1

Type RM Length L Ch R = 1,274597,2415,2415,2415
BEGIN DESCRIPTION:
Mapping XS a070693c
END DESCRIPTION:
XS GIS Cut Line= 3
      1653836.92      7011917.87      1654835.18      7010507.28
      1655703.23      7009758.59
#Sta/Elev= 30
  3888.9 1568.05  3945.0 1563.02  4123.4 1523.68  4381.9 1481.31  4806.6 1456.18
  4905.6 1437.01  4934.5 1438.53  4965.2 1424.39  4972.7 1423.39  5055.2 1424.39
  5071.2 1441.40  5092.5 1443.01  5158.5 1452.55  5236.3 1452.65  5279.2 1445.99
  5293.9 1435.40  5300.1 1439.25  5308.7 1432.87  5314.8 1437.17  5329.6 1432.47
  5350.5 1434.92  5371.4 1442.88  5380.1 1450.82  5466.2 1455.22  6190.6 1459.85
  6254.3 1465.20  6346.4 1483.91  6432.0 1495.42  6594.3 1508.04  6763.3 1511.72
#Mann=5,-1,0
  3888.9    0.05       0  4965.2    0.05       0  5055.2    0.05       0
  5092.5    0.12       0  5158.5    0.05       0
Bank Sta=4965.2,5055.2
Exp/Cntr=0.3,0.1

Type RM Length L Ch R = 1,272182,1850,1850,1850
BEGIN DESCRIPTION:
Mapping XS 6e7a28cb
END DESCRIPTION:
XS GIS Cut Line= 3
      1654439.71      7012800.34      1655537.36      7012884.06
      1657490.34      7011033.38
#Sta/Elev= 30
  2366.8 1508.65  2462.4 1505.39  2652.9 1489.06  2943.8 1477.84  3505.7 1474.36
  3901.8 1458.35  4283.7 1452.33  4828.3 1451.76  4878.6 1446.84  4912.1 1439.18
  4927.3 1437.93  4941.5 1428.41  4991.2 1428.05  4993.7 1424.33  4997.4 1423.33
  5038.7 1424.33  5062.0 1429.03  5076.1 1427.94  5155.3 1451.72  5203.2 1472.47
  5231.5 1479.21  5309.6 1514.82  5385.5 1523.05  5571.3 1537.95  5606.5 1545.90
  5719.7 1559.28  5833.0 1580.82  5868.2 1591.73  5945.9 1602.04  6158.2 1615.77
#Mann=7,-1,0
  2366.8    0.05       0  4878.6    0.12       0  4912.1    0.05       0
  4993.7    0.05       0  5038.7    0.05       0  5155.3    0.12       0
  5385.5    0.05       0
Bank Sta=4993.7,5038.7
Exp/Cntr=0.3,0.1

Type RM Length L Ch R = 1,270332,3838,3838,3838
BEGIN DESCRIPTION:
Clear Fork Brazos Rv 69.0
END DESCRIPTION:
XS GIS Cut Line= 3
      1654496.48      7013014.51      1657455.00      7013138.00
      1657955.01      7013138.00
#Sta/Elev= 30
  2037.0 1505.61  2075.5 1504.94  2240.6 1494.95  2345.8 1484.42  2556.0 1477.10
  2856.2 1473.91  3200.6 1474.79  3486.8 1459.62  3606.9 1455.57  4007.2 1454.88
  4227.4 1451.79  4407.6 1452.46  4635.6 1448.87  4787.9 1451.00  4817.9 1446.75
  4886.7 1443.94  4908.0 1442.71  4948.0 1424.15  4954.5 1422.59  4960.5 1421.59
  5026.5 1422.59  5038.1 1427.02  5103.2 1429.03  5118.1 1430.12  5138.1 1436.78
  5165.7 1439.00  5208.1 1443.41  5248.1 1454.10  5358.1 1509.13  5498.1 1515.25
#Mann=6,-1,0
  2037.0    0.05       0  4886.7    0.12       0  4954.5    0.05       0
  5026.5    0.12       0  5103.2    0.12       0  5165.7    0.05       0
Bank Sta=4954.5,5026.5
Exp/Cntr=0.3,0.1