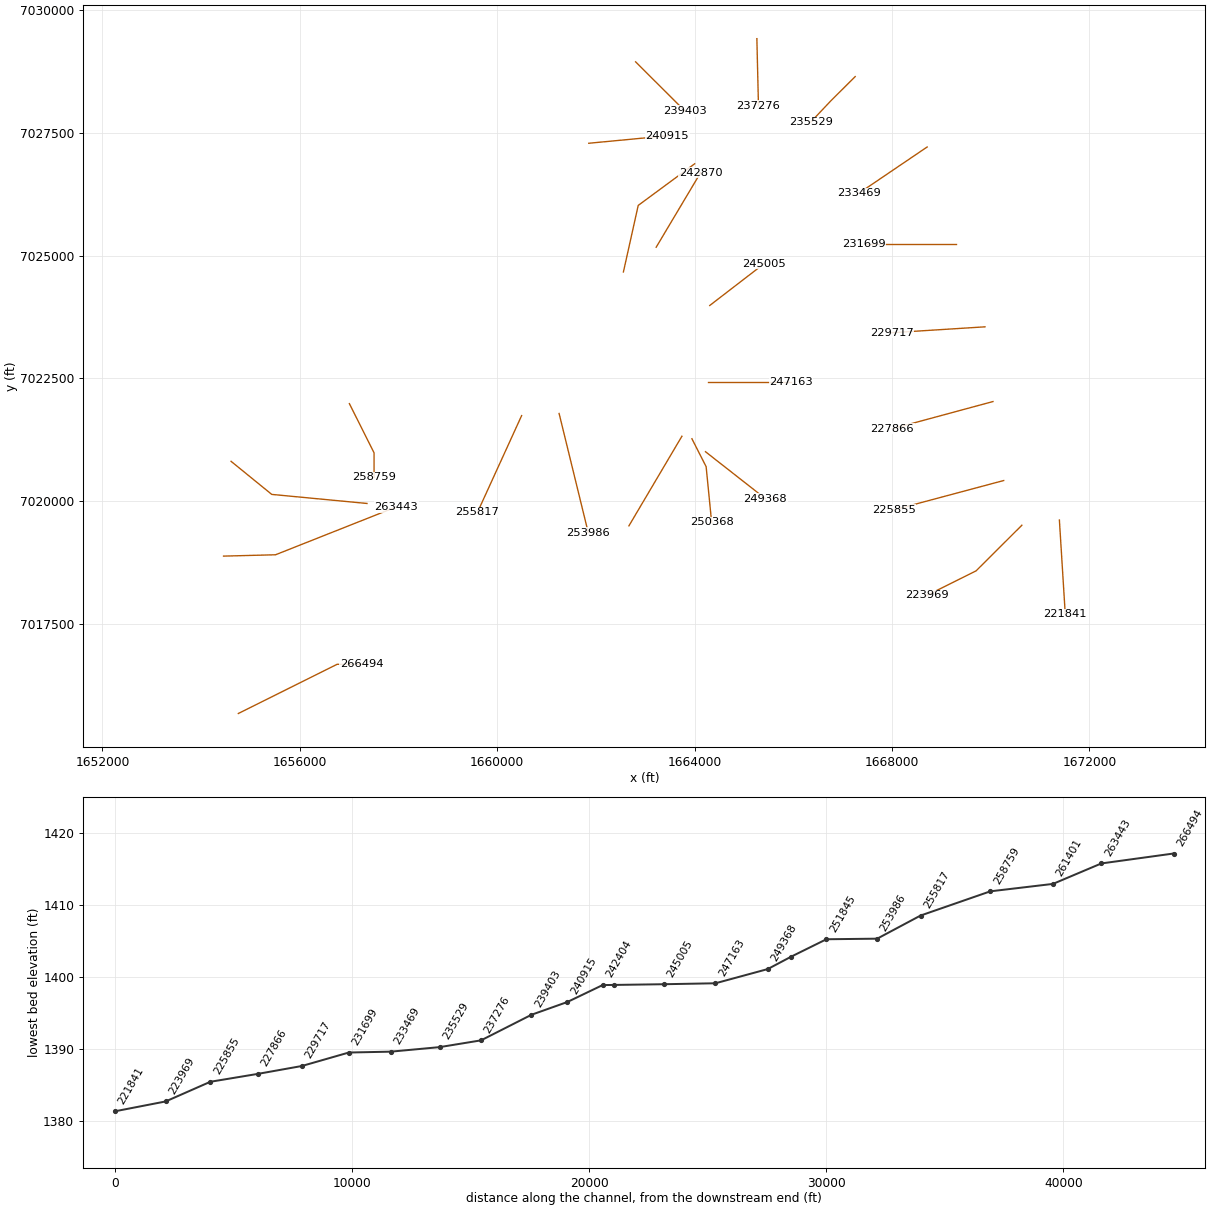
HEC-RAS study Clear Fork Brazos Rv.prj: Clear Fork Brazos Rv Base Level Engineering

--- Clear Fork Brazos Rv.g01 (geometry) --- (continued)

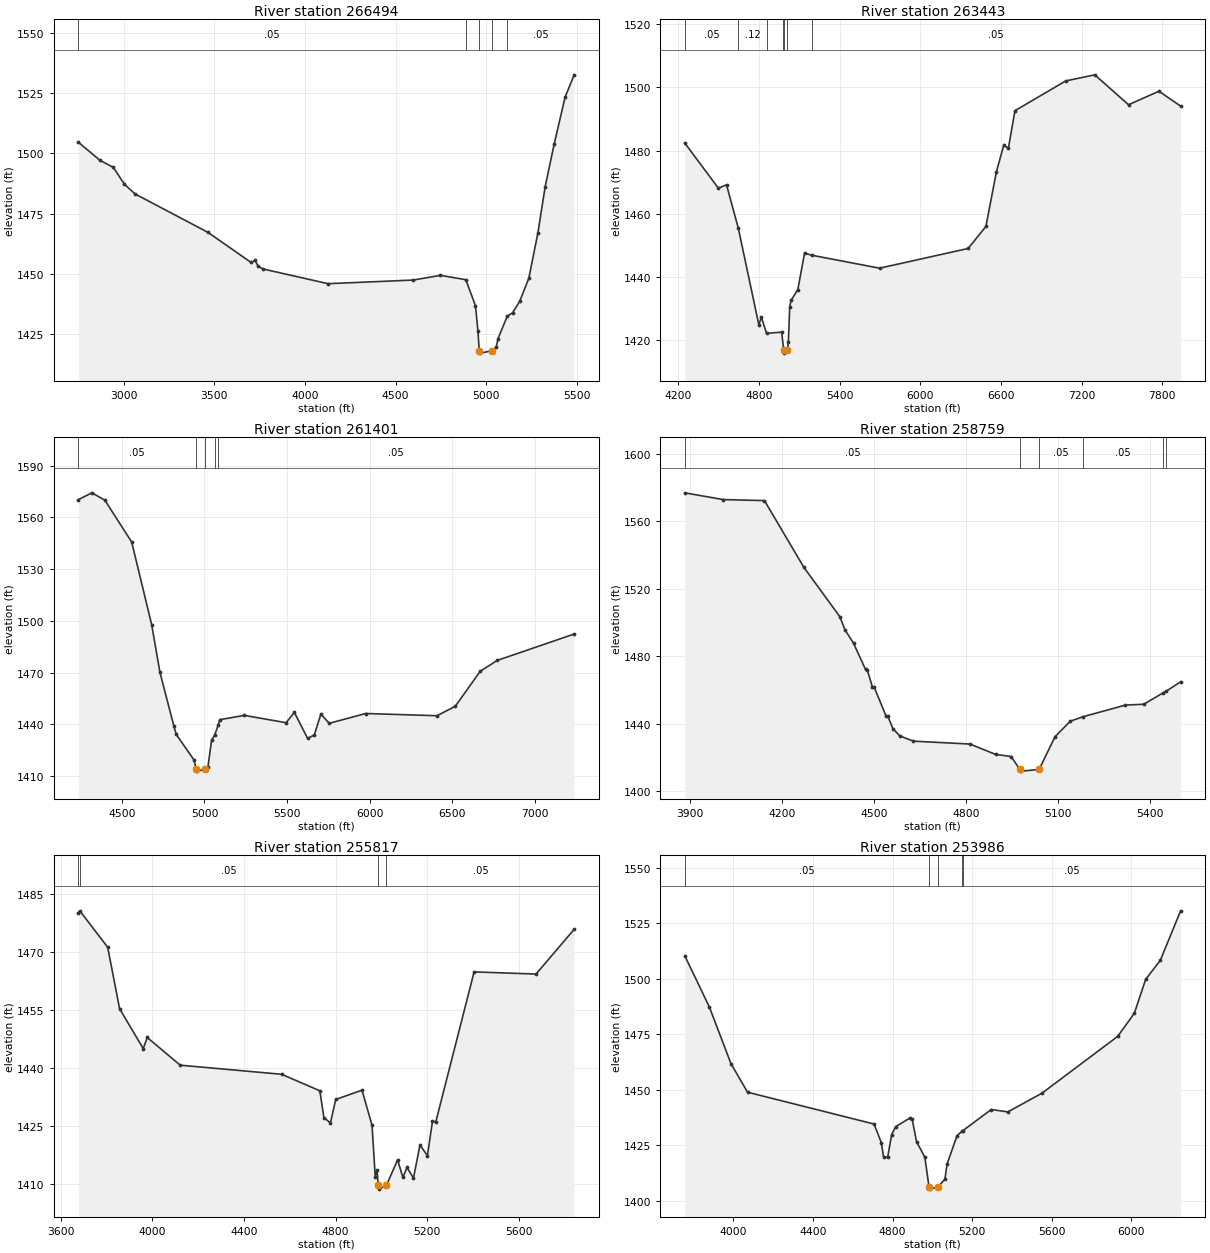
Type RM Length L Ch R = 1,266494,3051,3051,3051
BEGIN DESCRIPTION:
Clear Fork Brazos Rv 68.0
END DESCRIPTION:
XS GIS Cut Line= 3
      1654754.97      7015687.98      1656755.00      7016688.00
      1657255.00      7016688.00
#Sta/Elev= 30
  2749.4 1504.56  2869.6 1497.00  2942.3 1494.15  3003.8 1487.14  3062.5 1483.12
  3465.0 1467.19  3702.6 1454.74  3724.9 1455.56  3741.7 1453.12  3769.6 1452.02
  4127.4 1445.94  4597.0 1447.44  4747.9 1449.39  4887.7 1447.59  4940.8 1436.83
  4954.8 1426.18  4961.7 1418.17  4967.7 1417.17  5033.7 1418.17  5055.5 1419.67
  5065.5 1423.22  5116.6 1432.51  5145.5 1433.86  5185.5 1438.72  5235.5 1448.23
  5285.5 1467.02  5325.5 1486.10  5375.5 1503.87  5435.5 1523.21  5485.5 1532.47
#Mann=5,-1,0
  2749.4    0.05       0  4887.7    0.12       0  4961.7    0.07       0
  5033.7    0.12       0  5116.6    0.05       0
Bank Sta=4961.7,5033.7
Exp/Cntr=0.3,0.1

Type RM Length L Ch R = 1,263443,2042,2042,2042
BEGIN DESCRIPTION:
Clear Fork Brazos Rv 67.0
END DESCRIPTION:
XS GIS Cut Line= 3
      1654455.04      7018888.00      1655508.43      7018915.31
      1657955.02      7019888.01
#Sta/Elev= 30
  4249.3 1482.37  4499.3 1468.04  4559.4 1469.15  4647.4 1455.33  4799.4 1424.84
  4819.5 1427.11  4856.9 1422.07  4969.5 1422.43  4982.8 1417.57  4984.9 1416.79
  4987.1 1415.79  5011.9 1416.79  5019.5 1419.30  5029.5 1430.48  5039.5 1432.51
  5089.5 1435.89  5139.6 1447.46  5194.7 1446.80  5697.5 1442.71  6355.9 1448.95
  6488.1 1455.93  6566.4 1473.30  6620.4 1481.60  6655.4 1480.74  6704.0 1492.61
  7081.8 1502.05  7297.7 1503.98  7548.6 1494.50  7774.5 1498.78  7935.9 1494.07
#Mann=7,-1,0
  4249.3    0.05       0  4647.4    0.12       0  4856.9    0.05       0
  4982.8    0.12       0  4984.9    0.07       0  5011.9    0.12       0
  5194.7    0.05       0
Bank Sta=4984.9,5011.9
Exp/Cntr=0.3,0.1

Type RM Length L Ch R = 1,261401,2642,2642,2642
BEGIN DESCRIPTION:
Mapping XS f546d4a1
END DESCRIPTION:
XS GIS Cut Line= 3
      1654607.32      7020815.44      1655431.97      7020142.70
      1657361.74      7019958.39
#Sta/Elev= 30
  4236.0 1570.31  4317.9 1574.28  4396.2 1570.05  4559.2 1545.76  4680.5 1497.68
  4730.1 1470.28  4814.8 1438.99  4829.1 1434.21  4936.1 1419.50  4949.9 1413.95
  4954.4 1412.95  5003.9 1413.95  5020.9 1415.36  5043.1 1430.86  5062.5 1434.01
  5082.2 1439.47  5092.7 1442.78  5241.3 1445.26  5494.2 1441.03  5544.4 1447.00
  5624.8 1431.87  5664.9 1433.93  5705.1 1446.04  5755.3 1440.66  5976.3 1446.35
  6408.3 1445.07  6518.8 1450.53  6669.5 1470.77  6772.3 1477.11  7238.8 1492.42
#Mann=5,-1,0
  4236.0    0.05       0  4949.9    0.05       0  5003.9    0.05       0
  5062.5    0.12       0  5082.2    0.05       0
Bank Sta=4949.9,5003.9
Exp/Cntr=0.3,0.1

Type RM Length L Ch R = 1,258759,2942,2942,2942
BEGIN DESCRIPTION:
Clear Fork Brazos Rv 66.0
END DESCRIPTION:
XS GIS Cut Line= 3
      1657004.98      7021988.03      1657505.00      7020988.00
      1657505.00      7020487.97
#Sta/Elev= 30
  3882.3 1576.88  4008.1 1572.87  4142.3 1572.28  4270.9 1532.69  4388.2 1503.49
  4405.0 1495.66  4433.0 1487.74  4472.1 1472.18  4477.7 1471.96  4494.5 1461.84
  4500.1 1461.80  4539.2 1444.50  4544.8 1444.41  4561.5 1437.09  4583.9 1432.79
  4628.6 1429.68  4813.1 1427.97  4897.0 1421.81  4947.3 1420.58  4975.8 1412.92
  4981.0 1411.92  5038.8 1412.92  5090.4 1432.32  5140.4 1441.52  5182.2 1444.18
  5320.4 1451.06  5380.4 1451.58  5441.7 1458.15  5454.2 1459.40  5500.4 1464.88
#Mann=6,-1,0
  3882.3    0.05       0  4975.8    0.07       0  5038.8    0.05       0
  5182.2    0.05       0  5441.7    0.12       0  5454.2    0.05       0
Bank Sta=4975.8,5038.8
Exp/Cntr=0.3,0.1

Type RM Length L Ch R = 1,255817,1831,1831,1831
BEGIN DESCRIPTION:
Mapping XS cb9af0e1
END DESCRIPTION:
XS GIS Cut Line= 2
      1660495.61      7021744.58      1659599.31      7019775.26
#Sta/Elev= 30
  3677.2 1480.09  3683.6 1480.70  3805.3 1471.26  3857.2 1455.33  3960.4 1444.99
  3978.0 1447.87  4121.8 1440.69  4564.3 1438.33  4731.2 1434.05  4748.8 1427.10
  4777.4 1425.73  4800.4 1431.80  4915.0 1434.21  4958.9 1425.12  4972.8 1411.81
  4980.9 1413.54  4985.9 1409.56  4988.9 1408.56  5021.9 1409.56  5070.5 1416.14
  5093.6 1411.58  5111.1 1414.17  5139.7 1411.43  5168.2 1420.02  5200.6 1417.22
  5222.6 1426.13  5237.4 1426.05  5404.3 1464.87  5674.4 1464.31  5840.9 1475.90
#Mann=4,-1,0
  3677.2    0.12       0  3683.6    0.05       0  4985.9    0.05       0
  5021.9    0.05       0
Bank Sta=4985.9,5021.9
Exp/Cntr=0.3,0.1

Type RM Length L Ch R = 1,253986,2141,2141,2141
BEGIN DESCRIPTION:
Clear Fork Brazos Rv 65.0
END DESCRIPTION:
XS GIS Cut Line= 2
      1661254.99      7021788.04      1661845.17      7019367.45
#Sta/Elev= 30
  3755.9 1510.32  3879.5 1487.24  3987.8 1461.82  4071.2 1448.95  4706.9 1434.63
  4743.5 1426.25  4754.4 1419.98  4774.9 1419.62  4795.5 1429.88  4816.1 1433.49
  4888.2 1437.40  4898.5 1436.81  4920.5 1426.66  4962.2 1419.72  4983.1 1406.35
  4986.8 1405.35  5028.1 1406.35  5063.1 1409.84  5073.4 1416.51  5123.9 1429.42
  5149.6 1431.42  5152.8 1431.63  5295.8 1441.16  5379.2 1440.09  5551.1 1448.53
  5931.5 1474.09  6014.9 1484.47  6071.8 1499.73  6145.1 1508.21  6247.4 1530.54
#Mann=5,-1,0
  3755.9    0.05       0  4983.1    0.05       0  5028.1    0.05       0
  5149.6    0.12       0  5152.8    0.05       0
Bank Sta=4983.1,5028.1
Exp/Cntr=0.3,0.1

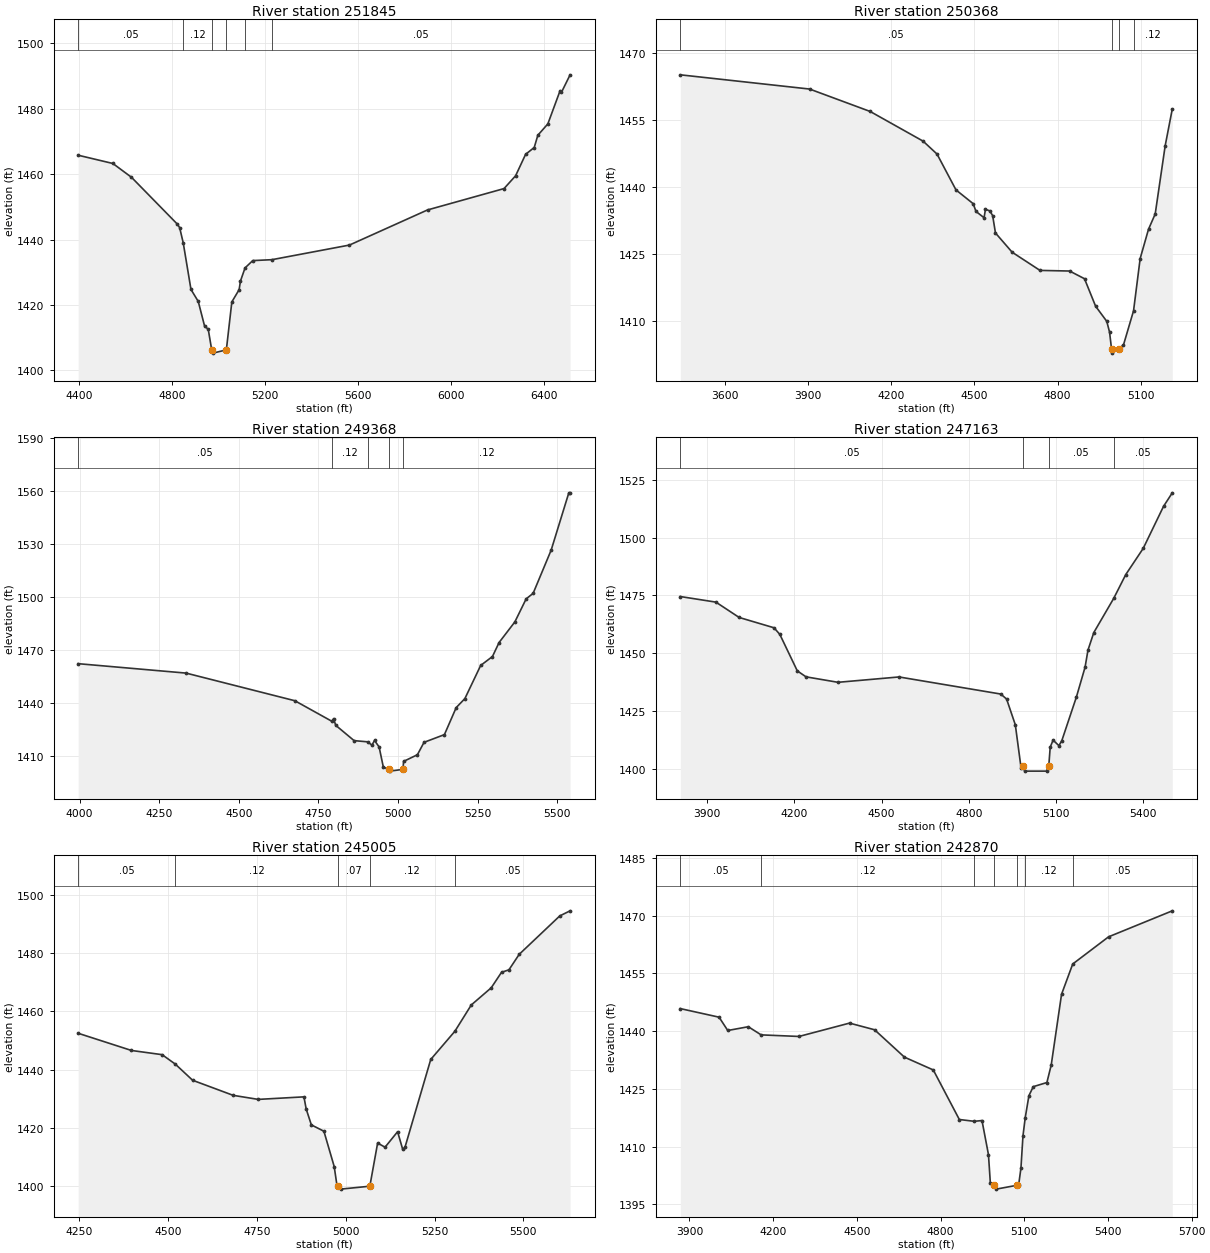
Type RM Length L Ch R = 1,251845,1477,1477,1477
BEGIN DESCRIPTION:
Mapping XS 1c7c4698
END DESCRIPTION:
XS GIS Cut Line= 2
      1663743.62      7021325.45      1662669.85      7019503.30
#Sta/Elev= 30
  4395.8 1465.78  4545.2 1463.25  4625.2 1459.03  4822.3 1444.71  4832.2 1443.64
  4847.6 1438.99  4880.9 1424.74  4912.2 1421.07  4939.5 1413.52  4955.1 1412.57
  4970.0 1406.27  4975.3 1405.27  5033.0 1406.27  5056.6 1420.93  5087.9 1424.67
  5093.7 1427.32  5113.4 1431.33  5146.5 1433.56  5228.8 1433.84  5562.2 1438.31
  5897.9 1449.05  6226.8 1455.58  6276.6 1459.50  6319.6 1466.06  6356.6 1468.14
  6372.2 1471.89  6415.2 1475.36  6467.9 1485.53  6473.7 1485.01  6510.8 1490.36
#Mann=6,-1,0
  4395.8    0.05       0  4847.6    0.12       0  4970.0    0.05       0
  5033.0    0.12       0  5113.4    0.12       0  5228.8    0.05       0
Bank Sta=4970,5033
Exp/Cntr=0.3,0.1

Type RM Length L Ch R = 1,250368,1000,1000,1000
BEGIN DESCRIPTION:
Mapping XS 7949a791
END DESCRIPTION:
XS GIS Cut Line= 3
      1663946.20      7021274.31      1664234.56      7020706.89
      1664346.13      7019572.56
#Sta/Elev= 30
  3438.1 1465.11  3904.8 1461.93  4123.7 1456.91  4314.6 1450.28  4364.9 1447.39
  4433.4 1439.37  4495.5 1436.29  4505.6 1434.56  4534.7 1433.15  4539.8 1435.03
  4555.8 1434.68  4565.8 1433.61  4575.9 1429.74  4636.1 1425.44  4736.7 1421.37
  4843.7 1421.23  4897.4 1419.51  4937.6 1413.35  4977.8 1409.98  4987.9 1407.56
  4994.9 1403.87  4997.2 1402.87  5021.9 1403.87  5038.1 1404.69  5074.5 1412.34
  5098.4 1424.03  5128.5 1430.57  5152.7 1433.99  5188.8 1449.28  5214.4 1457.47
#Mann=4,-1,0
  3438.1    0.05       0  4994.9    0.05       0  5021.9    0.05       0
  5074.5    0.12       0
Bank Sta=4994.9,5021.9
Exp/Cntr=0.3,0.1

Type RM Length L Ch R = 1,249368,2205,2205,2205
BEGIN DESCRIPTION:
Mapping XS 457d8ec2
END DESCRIPTION:
XS GIS Cut Line= 2
      1664221.05      7021010.74      1665436.31      7020055.90
#Sta/Elev= 30
  3995.3 1462.14  4334.4 1456.79  4676.1 1441.10  4791.9 1429.48  4798.0 1430.94
  4804.4 1427.17  4862.2 1418.45  4904.9 1417.76  4918.3 1415.89  4926.4 1418.54
  4940.8 1414.88  4954.1 1403.43  4970.8 1402.13  4974.6 1401.13  5015.8 1402.13
  5017.7 1406.66  5061.1 1410.43  5081.9 1417.48  5146.0 1421.86  5183.0 1437.21
  5210.2 1442.29  5259.9 1461.13  5296.9 1466.20  5317.7 1474.15  5367.4 1485.89
  5402.7 1498.93  5424.7 1502.08  5481.3 1526.60  5536.8 1559.15  5540.8 1559.15
#Mann=5,-1,0
  3995.3    0.05       0  4791.9    0.12       0  4904.9    0.05       0
  4970.8    0.05       0  5015.8    0.12       0
Bank Sta=4970.8,5015.8
Exp/Cntr=0.3,0.1

Type RM Length L Ch R = 1,247163,2158,2158,2158
BEGIN DESCRIPTION:
Clear Fork Brazos Rv 64.0
END DESCRIPTION:
XS GIS Cut Line= 4
      1664262.67      7022438.00      1664955.00      7022438.00
      1665455.00      7022438.00      1665954.97      7022438.00
#Sta/Elev= 30
  3807.5 1474.54  3929.8 1472.13  4009.8 1465.51  4129.8 1461.05  4149.8 1458.18
  4209.8 1442.45  4239.8 1439.87  4349.8 1437.51  4559.8 1439.82  4909.8 1432.44
  4929.8 1430.28  4959.8 1419.17  4979.8 1400.37  4984.8 1401.16  4992.3 1399.16
  5067.3 1399.16  5074.8 1401.16  5079.8 1409.52  5089.8 1412.54  5109.8 1410.15
  5119.8 1412.33  5169.8 1431.10  5199.8 1444.06  5209.8 1451.43  5229.8 1458.99
  5298.2 1473.73  5339.8 1484.04  5399.8 1495.34  5469.8 1513.51  5499.8 1519.32
#Mann=4,-1,0
  3807.5    0.05       0  4984.8    0.03       0  5074.8    0.05       0
  5298.2    0.05       0
Bank Sta=4984.8,5074.8
Exp/Cntr=0.3,0.1

Type RM Length L Ch R = 1,245005,2135,2135,2135
BEGIN DESCRIPTION:
Mapping XS 14316226
END DESCRIPTION:
XS GIS Cut Line= 2
      1664307.87      7023983.87      1665403.72      7024830.17
#Sta/Elev= 30
  4247.0 1452.46  4397.1 1446.56  4483.4 1445.12  4520.5 1441.88  4569.2 1436.35
  4683.3 1431.18  4753.9 1429.79  4882.5 1430.66  4888.9 1426.47  4903.4 1421.05
  4938.7 1418.88  4967.7 1406.77  4975.8 1400.03  4978.0 1400.03  4985.5 1399.03
  5068.0 1400.03  5089.9 1414.82  5110.8 1413.40  5146.1 1418.71  5160.6 1412.62
  5166.9 1413.38  5239.4 1443.48  5307.3 1453.14  5353.5 1462.16  5409.6 1468.04
  5438.6 1473.35  5459.5 1474.21  5488.4 1479.52  5602.6 1492.69  5631.6 1494.43
#Mann=5,-1,0
  4247.0    0.05       0  4520.5    0.12       0  4978.0    0.07       0
  5068.0    0.12       0  5307.3    0.05       0
Bank Sta=4978,5068
Exp/Cntr=0.3,0.1

Type RM Length L Ch R = 1,242870,466,466,466
BEGIN DESCRIPTION:
Mapping XS 5613bd06
END DESCRIPTION:
XS GIS Cut Line= 3
      1663222.18      7025168.64      1663472.34      7025589.75
      1664122.60      7026684.36
#Sta/Elev= 30
  3867.6 1445.86  4006.4 1443.63  4037.5 1440.17  4111.1 1441.15  4157.2 1439.03
  4292.7 1438.62  4473.9 1442.09  4563.6 1440.36  4670.7 1433.24  4774.1 1429.91
  4867.4 1417.03  4921.0 1416.56  4948.6 1416.76  4971.8 1407.91  4978.5 1400.57
  4992.8 1399.93  4999.6 1398.93  5073.8 1399.93  5079.8 1399.93  5088.2 1404.39
  5095.4 1412.71  5103.5 1417.47  5116.8 1423.23  5132.4 1425.57  5181.2 1426.64
  5196.7 1431.19  5233.7 1449.58  5273.8 1457.46  5402.2 1464.52  5630.6 1471.28
#Mann=7,-1,0
  3867.6    0.05       0  4157.2    0.12       0  4921.0    0.05       0
  4992.8    0.03       0  5073.8    0.05       0  5103.5    0.12       0
  5273.8    0.05       0
Bank Sta=4992.8,5073.8
Exp/Cntr=0.3,0.1

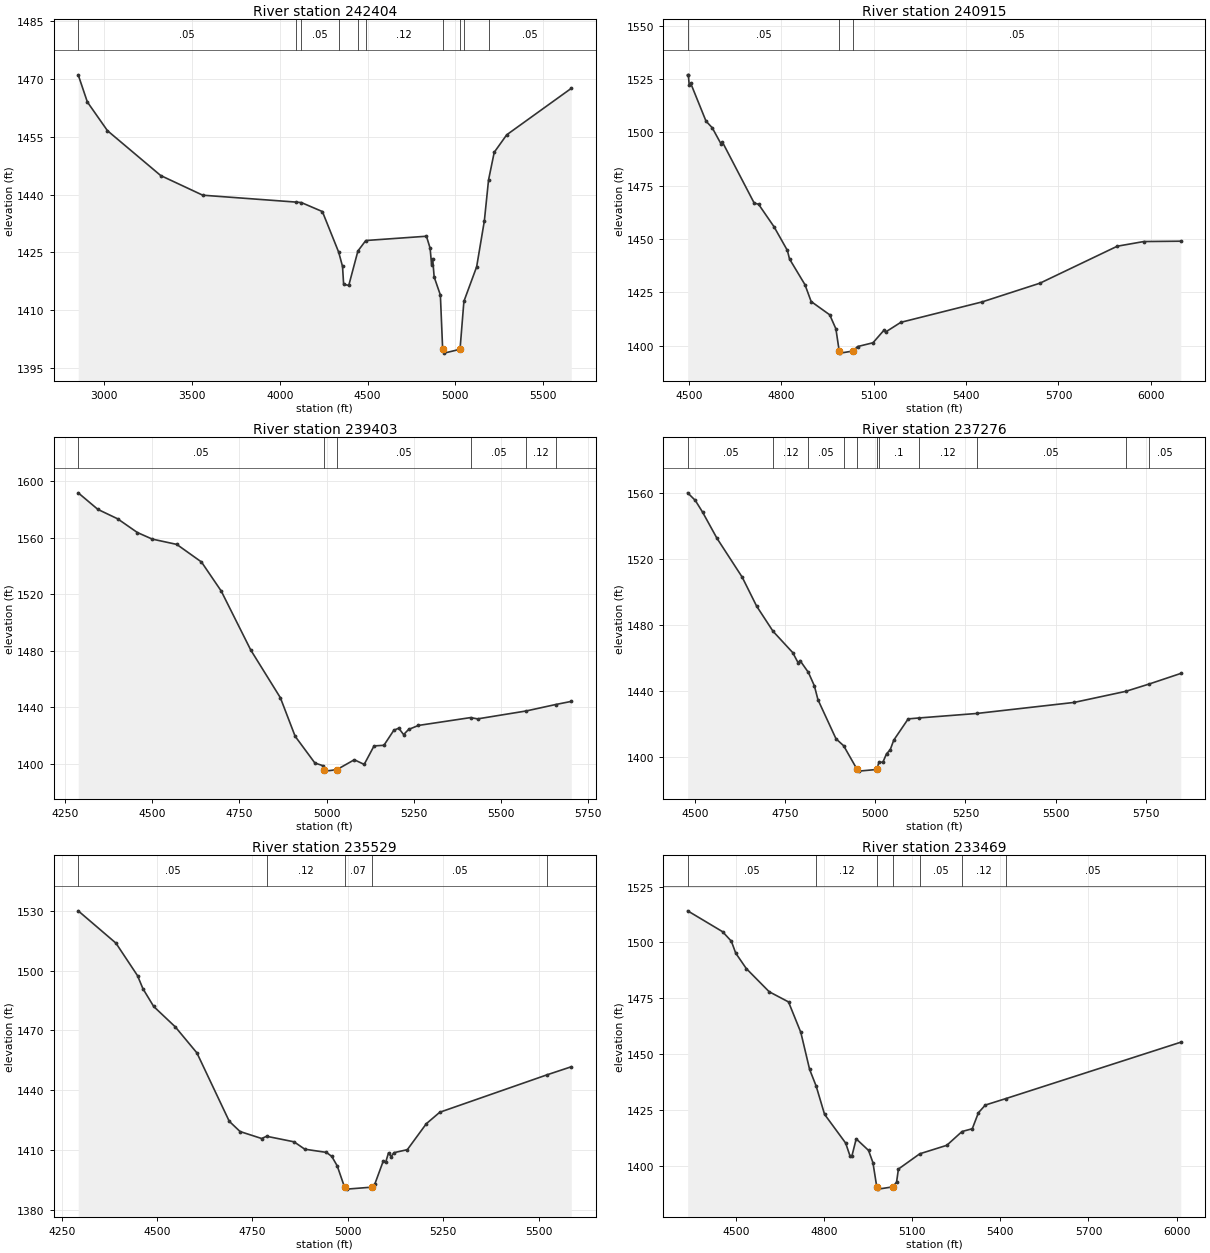
Type RM Length L Ch R = 1,242404,1489,1489,1489
BEGIN DESCRIPTION:
Mapping XS 25fb7d25
END DESCRIPTION:
XS GIS Cut Line= 3
      1662558.00      7024665.42      1662857.89      7026018.23
      1664002.05      7026864.72
#Sta/Elev= 30
  2851.3 1471.00  2903.4 1463.97  3017.8 1456.54  3321.3 1444.91  3560.7 1439.82
  4093.4 1438.03  4123.2 1437.90  4242.3 1435.58  4335.3 1425.04  4357.1 1421.35
  4363.3 1416.72  4392.6 1416.46  4444.7 1425.37  4489.6 1428.08  4835.1 1429.19
  4855.9 1426.09  4864.3 1421.86  4870.5 1423.40  4878.9 1418.65  4914.4 1413.96
  4927.4 1399.91  4935.7 1398.91  5026.4 1399.91  5048.4 1412.32  5121.0 1421.27
  5164.9 1433.16  5188.8 1443.77  5221.2 1450.94  5292.2 1455.46  5660.2 1467.50
#Mann=10,-1,0
  2851.3    0.05       0  4093.4    0.12       0  4123.2    0.05       0
  4335.3    0.12       0  4444.7    0.05       0  4489.6    0.12       0
  4927.4    0.03       0  5026.4    0.12       0  5048.4    0.12       0
  5188.8    0.05       0
Bank Sta=4927.4,5026.4
Exp/Cntr=0.3,0.1

Type RM Length L Ch R = 1,240915,1512,1512,1512
BEGIN DESCRIPTION:
Mapping XS af8a4a53
END DESCRIPTION:
XS GIS Cut Line= 2
      1661855.58      7027282.46      1663450.27      7027434.33
#Sta/Elev= 30
  4495.4 1526.96  4497.6 1526.96  4500.5 1522.06  4505.5 1522.94  4555.1 1505.24
  4575.2 1502.17  4603.5 1494.67  4608.5 1495.41  4711.4 1466.91  4725.9 1466.29
  4776.1 1455.75  4819.4 1444.67  4826.3 1440.68  4876.5 1428.63  4896.6 1420.74
  4956.9 1414.51  4977.0 1407.93  4987.7 1397.56  4991.5 1396.56  5032.7 1397.56
  5047.3 1399.63  5097.5 1401.42  5133.3 1407.33  5138.4 1406.45  5187.9 1410.99
  5452.3 1420.57  5640.0 1429.34  5891.1 1446.66  5977.1 1448.84  6097.3 1449.01
#Mann=3,-1,0
  4495.4    0.05       0  4987.7    0.05       0  5032.7    0.05       0
Bank Sta=4987.7,5032.7
Exp/Cntr=0.3,0.1

Type RM Length L Ch R = 1,239403,2127,2127,2127
BEGIN DESCRIPTION:
Clear Fork Brazos Rv 62.0
END DESCRIPTION:
XS GIS Cut Line= 3
      1662805.03      7028937.97      1663305.00      7028438.00
      1663805.02      7027937.98
#Sta/Elev= 30
  4287.4 1591.81  4343.9 1580.08  4400.5 1573.42  4457.1 1563.71  4499.5 1559.08
  4570.2 1555.29  4640.9 1542.86  4697.5 1522.32  4782.3 1480.52  4867.2 1446.76
  4909.6 1419.46  4966.2 1400.55  4990.9 1398.50  4992.8 1395.79  4995.8 1394.79
  5028.8 1395.79  5079.3 1402.84  5107.6 1399.54  5135.9 1412.64  5164.2 1413.08
  5192.5 1423.68  5206.6 1425.20  5220.7 1420.65  5234.9 1424.28  5263.2 1427.14
  5412.7 1432.69  5432.9 1431.78  5572.0 1437.37  5656.3 1441.92  5701.6 1444.16
#Mann=6,-1,0
  4287.4    0.05       0  4992.8    0.07       0  5028.8    0.05       0
  5412.7    0.05       0  5572.0    0.12       0  5656.3    0.05       0
Bank Sta=4992.8,5028.8
Exp/Cntr=0.3,0.1

Type RM Length L Ch R = 1,237276,1747,1747,1747
BEGIN DESCRIPTION:
Mapping XS b8ccc999
END DESCRIPTION:
XS GIS Cut Line= 2
      1665262.70      7029409.20      1665295.24      7028042.48
#Sta/Elev= 30
  4479.8 1560.24  4501.0 1555.63  4521.0 1548.58  4561.0 1532.66  4631.0 1509.03
  4671.1 1491.40  4716.6 1476.14  4771.1 1463.22  4786.3 1456.94  4791.3 1458.40
  4814.5 1451.20  4831.1 1443.04  4841.1 1434.59  4891.1 1410.87  4912.3 1406.65
  4949.7 1392.24  4954.2 1391.24  5003.7 1392.24  5010.1 1396.55  5021.2 1396.71
  5031.2 1401.81  5041.2 1404.11  5051.2 1410.06  5091.2 1422.96  5120.3 1423.51
  5281.2 1426.25  5551.3 1432.96  5694.7 1439.70  5758.9 1444.11  5846.9 1450.56
#Mann=11,-1,0
  4479.8    0.05       0  4716.6    0.12       0  4814.5    0.05       0
  4912.3    0.12       0  4949.7    0.07       0  5003.7    0.12       0
  5010.1     0.1       0  5120.3    0.12       0  5281.2    0.05       0
  5694.7    0.12       0  5758.9    0.05       0
Bank Sta=4949.7,5003.7
Exp/Cntr=0.3,0.1

Type RM Length L Ch R = 1,235529,2060,2060,2060
BEGIN DESCRIPTION:
Clear Fork Brazos Rv 61.0
END DESCRIPTION:
XS GIS Cut Line= 3
      1667254.97      7028637.97      1666755.00      7028138.00
      1666353.54      7027712.16
#Sta/Elev= 30
  4293.3 1530.00  4392.2 1513.79  4448.8 1497.45  4463.0 1490.89  4491.2 1481.98
  4547.8 1471.74  4604.4 1458.69  4689.2 1424.36  4717.5 1419.21  4774.1 1415.71
  4787.1 1416.83  4858.9 1414.05  4887.2 1410.34  4943.8 1408.74  4957.9 1406.71
  4972.1 1401.99  4991.3 1391.30  4997.3 1390.30  5063.3 1391.30  5071.0 1393.01
  5092.4 1404.19  5099.3 1403.90  5106.6 1408.52  5113.4 1406.62  5120.7 1408.59
  5155.9 1410.11  5205.7 1423.15  5240.9 1428.89  5522.3 1447.70  5585.6 1451.73
#Mann=5,-1,0
  4293.3    0.05       0  4787.1    0.12       0  4991.3    0.07       0
  5063.3    0.05       0  5522.3    0.05       0
Bank Sta=4991.3,5063.3
Exp/Cntr=0.3,0.1

Type RM Length L Ch R = 1,233469,1770,1770,1770
BEGIN DESCRIPTION:
Mapping XS bb9c758b
END DESCRIPTION:
XS GIS Cut Line= 2
      1668713.25      7027206.52      1667324.72      7026262.75
#Sta/Elev= 30
  4335.3 1514.15  4454.2 1504.82  4484.1 1500.56  4499.0 1495.22  4535.0 1488.32
  4612.9 1477.96  4678.7 1473.41  4720.6 1459.77  4750.5 1443.24  4772.8 1435.77
  4801.4 1423.13  4873.2 1410.28  4888.2 1404.47  4894.2 1404.32  4909.2 1412.16
  4951.1 1407.00  4966.1 1401.54  4979.2 1390.67  4983.7 1389.67  5033.2 1390.67
  5046.6 1392.80  5052.9 1398.65  5125.5 1405.47  5217.6 1409.27  5269.5 1415.44
  5304.4 1416.68  5325.3 1423.84  5348.8 1427.28  5418.0 1430.14  6014.2 1455.38
#Mann=7,-1,0
  4335.3    0.05       0  4772.8    0.12       0  4979.2    0.07       0
  5033.2    0.12       0  5125.5    0.05       0  5269.5    0.12       0
  5418.0    0.05       0
Bank Sta=4979.2,5033.2
Exp/Cntr=0.3,0.1

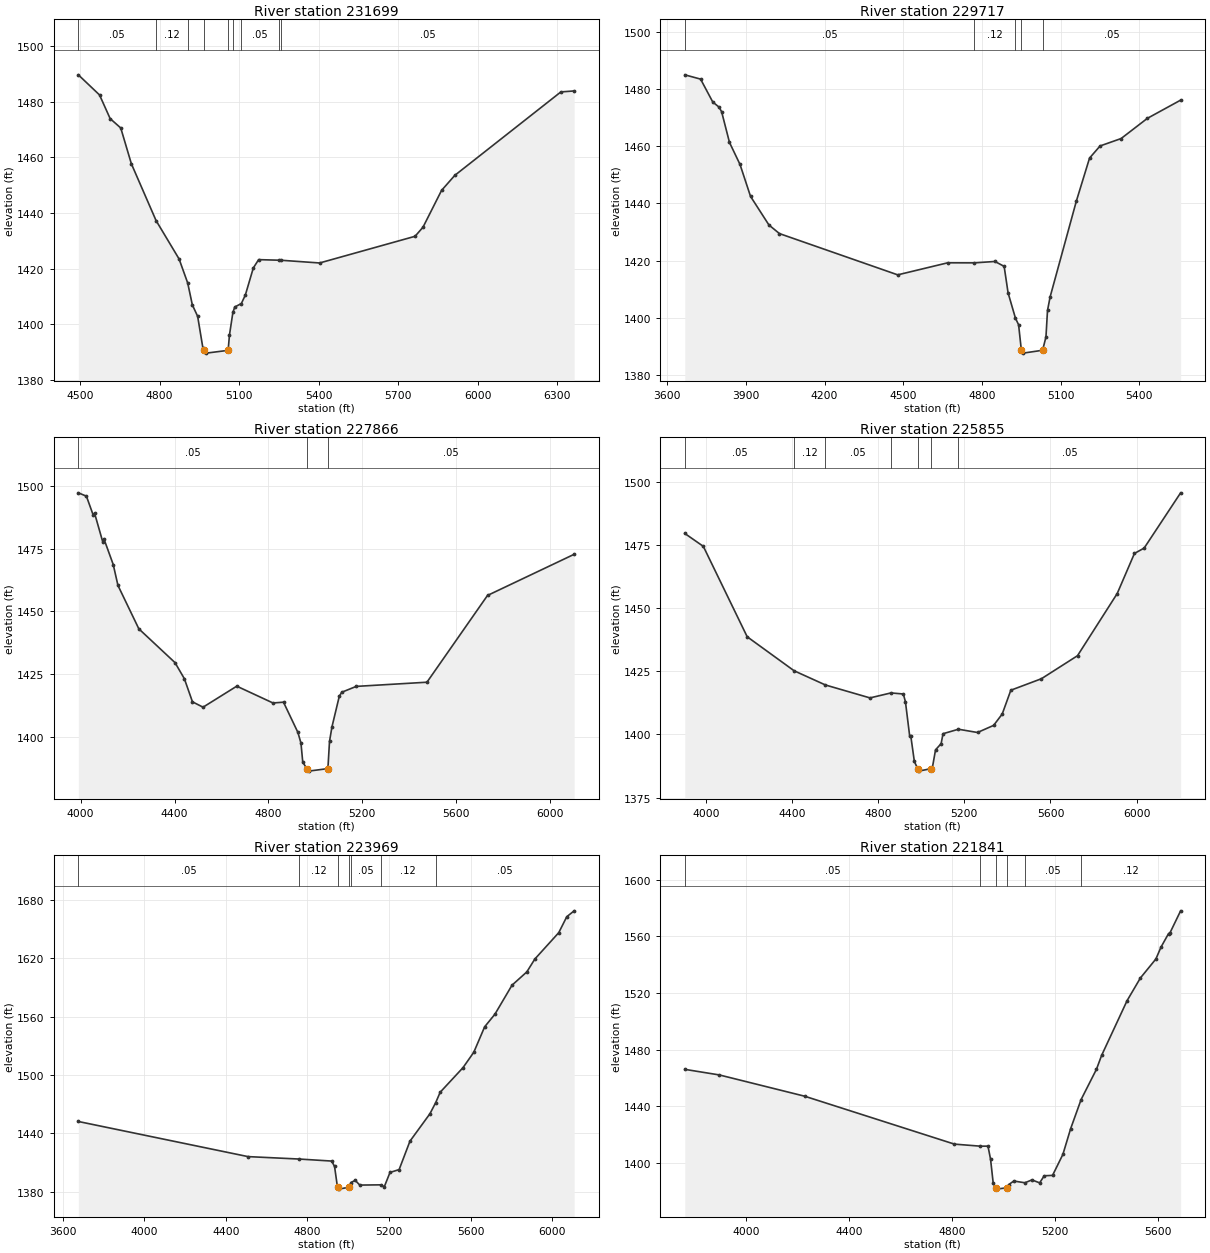
Type RM Length L Ch R = 1,231699,1982,1982,1982
BEGIN DESCRIPTION:
Clear Fork Brazos Rv 60.0
END DESCRIPTION:
XS GIS Cut Line= 4
      1669304.98      7025238.00      1668805.00      7025238.00
      1668305.00      7025238.00      1667434.88      7025238.00
#Sta/Elev= 30
  4493.4 1489.72  4573.4 1482.47  4613.4 1473.96  4653.4 1470.59  4693.4 1457.71
  4786.5 1437.28  4873.4 1423.44  4906.0 1414.76  4923.4 1406.91  4943.4 1402.80
  4963.4 1391.29  4968.4 1390.55  4975.9 1389.55  5058.4 1390.55  5063.4 1396.04
  5076.3 1404.18  5083.4 1406.15  5108.3 1407.41  5123.4 1410.48  5153.4 1420.21
  5173.4 1423.20  5248.9 1423.00  5256.5 1422.99  5403.4 1422.00  5763.4 1431.60
  5793.4 1434.88  5863.4 1448.12  5913.4 1453.54  6313.4 1483.57  6363.5 1483.92
#Mann=9,-1,0
  4493.4    0.05       0  4786.5    0.12       0  4906.0    0.05       0
  4968.4    0.03       0  5058.4    0.05       0  5076.3    0.12       0
  5108.3    0.05       0  5248.9    0.12       0  5256.5    0.05       0
Bank Sta=4968.4,5058.4
Exp/Cntr=0.3,0.1

Type RM Length L Ch R = 1,229717,1851,1851,1851
BEGIN DESCRIPTION:
Mapping XS 8812f60a
END DESCRIPTION:
XS GIS Cut Line= 2
      1669885.07      7023549.81      1667998.54      7023430.55
#Sta/Elev= 30
  3667.4 1484.99  3727.6 1483.49  3774.0 1475.49  3797.7 1473.72  3807.7 1472.11
  3837.8 1461.34  3877.9 1453.65  3918.0 1442.49  3988.1 1432.49  4028.2 1429.48
  4479.1 1415.05  4669.5 1419.26  4771.5 1419.24  4849.8 1419.73  4884.9 1418.02
  4899.9 1408.75  4928.0 1399.90  4940.0 1397.59  4950.5 1388.68  4957.3 1387.68
  5031.5 1388.68  5044.3 1393.33  5050.2 1402.60  5060.2 1407.35  5160.4 1440.91
  5210.5 1455.88  5250.6 1460.12  5330.8 1462.71  5431.0 1469.78  5557.7 1476.14
#Mann=5,-1,0
  3667.4    0.05       0  4771.5    0.12       0  4928.0    0.05       0
  4950.5    0.03       0  5031.5    0.05       0
Bank Sta=4950.5,5031.5
Exp/Cntr=0.3,0.1

Type RM Length L Ch R = 1,227866,2011,2011,2011
BEGIN DESCRIPTION:
Mapping XS fc679ce0
END DESCRIPTION:
XS GIS Cut Line= 2
      1670047.88      7022030.73      1668008.97      7021477.62
#Sta/Elev= 30
  3990.1 1497.11  4024.5 1495.78  4053.9 1488.16  4059.1 1489.08  4093.8 1477.75
  4098.9 1478.89  4138.8 1468.63  4158.9 1460.33  4247.9 1443.10  4402.0 1429.68
  4441.8 1423.31  4476.4 1414.11  4521.5 1411.98  4665.2 1420.33  4819.3 1413.66
  4864.3 1413.97  4925.6 1401.97  4938.7 1397.72  4946.3 1390.17  4963.5 1387.59
  4971.0 1386.59  5053.5 1387.59  5060.3 1398.37  5070.7 1404.15  5101.8 1416.24
  5112.1 1417.90  5174.3 1420.24  5475.5 1421.90  5733.5 1456.36  6102.7 1472.70
#Mann=3,-1,0
  3990.1    0.05       0  4963.5    0.03       0  5053.5    0.05       0
Bank Sta=4963.5,5053.5
Exp/Cntr=0.3,0.1

Type RM Length L Ch R = 1,225855,1886,1886,1886
BEGIN DESCRIPTION:
Mapping XS 28527f64
END DESCRIPTION:
XS GIS Cut Line= 2
      1670264.90      7020424.82      1668040.47      7019828.02
#Sta/Elev= 30
  3901.4 1479.56  3987.5 1474.45  4191.2 1438.67  4409.3 1425.20  4554.9 1419.58
  4761.6 1414.47  4858.9 1416.44  4916.5 1416.02  4926.3 1412.92  4946.1 1399.28
  4951.3 1399.31  4967.7 1389.32  4982.9 1386.49  4988.2 1385.49  5045.9 1386.49
  5050.6 1386.49  5066.1 1393.92  5092.0 1396.36  5100.9 1400.30  5172.5 1402.07
  5261.0 1400.78  5335.8 1403.59  5375.8 1408.09  5415.8 1417.51  5557.9 1422.06
  5725.5 1431.17  5909.9 1455.77  5990.0 1471.65  6035.1 1473.77  6204.5 1495.64
#Mann=7,-1,0
  3901.4    0.05       0  4409.3    0.12       0  4554.9    0.05       0
  4858.9    0.12       0  4982.9    0.07       0  5045.9    0.12       0
  5172.5    0.05       0
Bank Sta=4982.9,5045.9
Exp/Cntr=0.3,0.1

Type RM Length L Ch R = 1,223969,2128,2128,2128
BEGIN DESCRIPTION:
Clear Fork Brazos Rv 58.0
END DESCRIPTION:
XS GIS Cut Line= 4
      1670633.21      7019516.21      1670205.00      7019088.00
      1669705.00      7018588.00      1668705.02      7018088.01
#Sta/Elev= 30
  3677.3 1452.30  4509.2 1416.19  4760.9 1413.68  4919.3 1411.61  4933.4 1406.06
  4947.6 1384.92  4950.0 1384.76  4954.5 1382.76  5004.0 1384.76  5013.7 1389.53
  5034.7 1391.78  5057.1 1386.92  5159.9 1387.17  5177.3 1385.22  5205.2 1399.93
  5249.9 1402.84  5303.0 1432.06  5400.9 1460.24  5429.5 1471.82  5451.2 1482.37
  5563.0 1507.63  5616.1 1523.53  5669.2 1549.64  5719.5 1562.59  5803.4 1592.45
  5876.0 1606.10  5915.2 1619.31  6032.6 1646.47  6071.7 1662.81  6108.0 1668.89
#Mann=7,-1,0
  3677.3    0.05       0  4760.9    0.12       0  4950.0    0.07       0
  5004.0    0.12       0  5013.7    0.05       0  5159.9    0.12       0
  5429.5    0.05       0
Bank Sta=4950,5004
Exp/Cntr=0.3,0.1

Type RM Length L Ch R = 1,221841,1718,1718,1718
BEGIN DESCRIPTION:
Mapping XS 901edd92
END DESCRIPTION:
XS GIS Cut Line= 2
      1671393.34      7019621.86      1671512.65      7017702.16
#Sta/Elev= 30
  3762.9 1466.07  3897.0 1462.11  4227.7 1447.09  4808.8 1413.21  4908.8 1411.77
  4939.0 1411.79  4949.0 1402.55  4959.1 1385.91  4968.3 1382.40  4972.0 1381.40
  5013.3 1382.40  5019.2 1384.58  5039.2 1387.11  5082.4 1385.90  5109.4 1387.93
  5139.4 1385.82  5157.2 1390.84  5189.5 1391.12  5229.6 1405.96  5259.6 1424.09
  5300.3 1444.74  5359.8 1466.12  5379.9 1475.96  5478.7 1514.66  5530.2 1530.64
  5590.3 1544.06  5610.3 1552.51  5639.5 1562.03  5644.5 1562.36  5686.3 1578.12
#Mann=6,-1,0
  3762.9    0.05       0  4908.8    0.12       0  4968.3    0.07       0
  5013.3    0.12       0  5082.4    0.05       0  5300.3    0.12       0
Bank Sta=4968.3,5013.3
Exp/Cntr=0.3,0.1