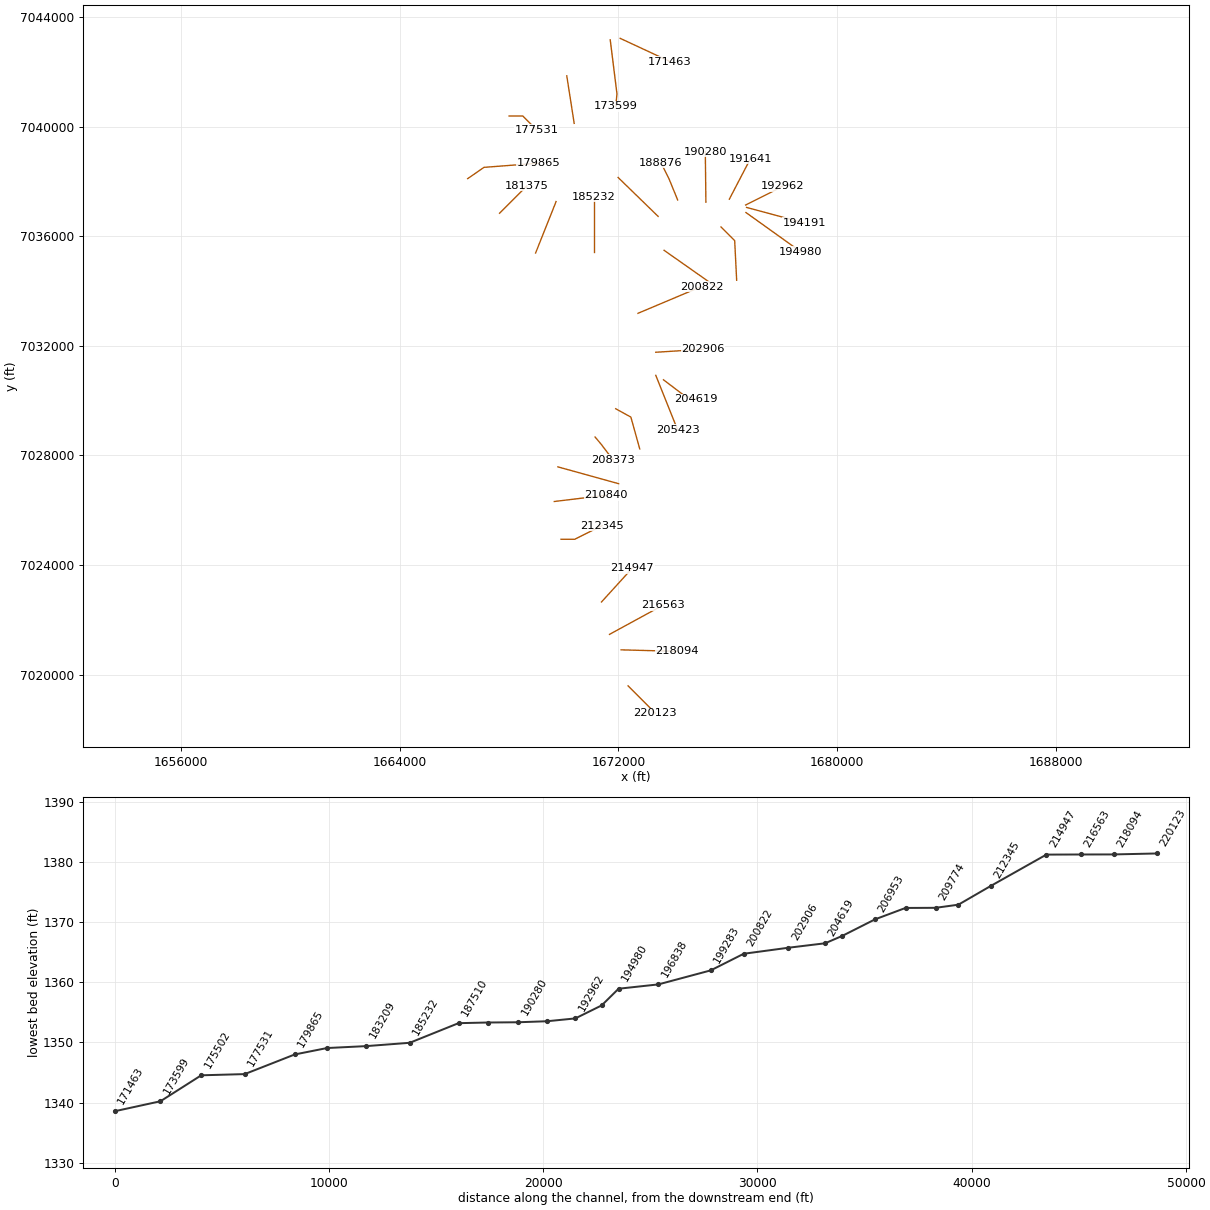
HEC-RAS study Clear Fork Brazos Rv.prj: Clear Fork Brazos Rv Base Level Engineering

--- Clear Fork Brazos Rv.g01 (geometry) --- (continued)

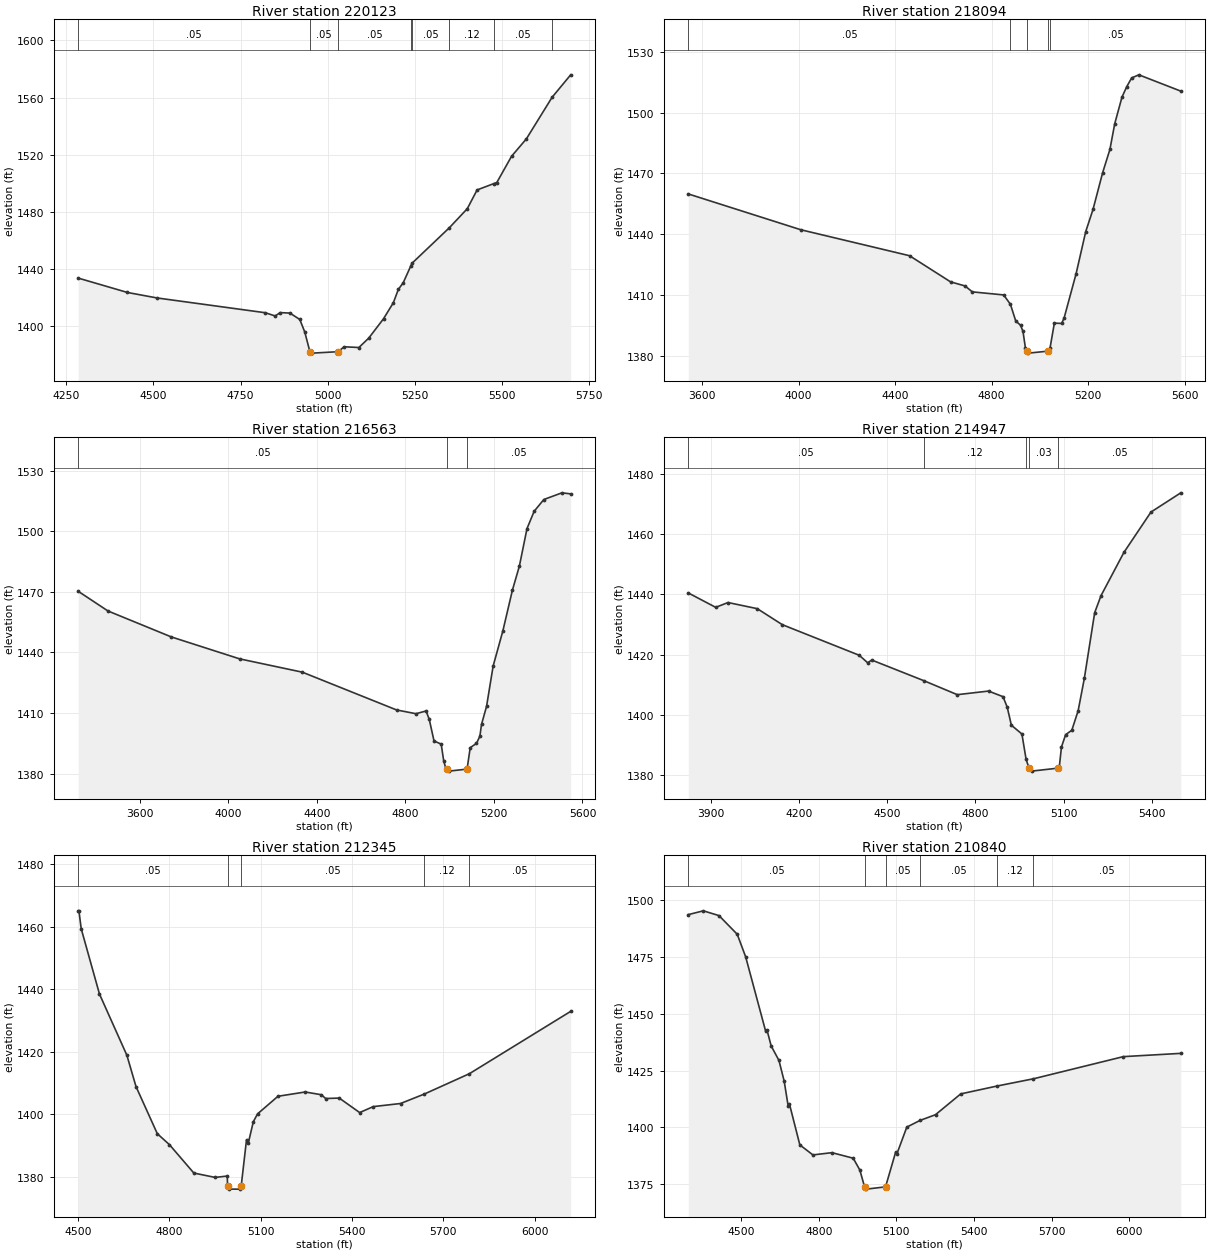
Type RM Length L Ch R = 1,220123,2029,2029,2029
BEGIN DESCRIPTION:
Clear Fork Brazos Rv 57.0
END DESCRIPTION:
XS GIS Cut Line= 3
      1672354.98      7019588.02      1672855.00      7019088.00
      1673354.97      7018588.03
#Sta/Elev= 30
  4283.7 1433.85  4425.2 1423.79  4510.0 1419.96  4821.1 1409.62  4849.4 1407.36
  4863.6 1409.71  4891.8 1409.38  4920.1 1404.90  4934.3 1396.18  4949.1 1382.38
  4955.8 1381.38  5030.1 1382.38  5047.4 1385.82  5089.8 1385.31  5118.1 1391.89
  5160.5 1405.42  5188.8 1416.65  5203.0 1425.91  5217.1 1430.61  5239.2 1442.57
  5242.2 1444.19  5349.7 1469.09  5401.0 1482.37  5429.2 1495.48  5476.6 1499.85
  5485.8 1500.67  5528.2 1519.04  5570.7 1531.19  5644.6 1560.29  5697.9 1575.96
#Mann=8,-1,0
  4283.7    0.05       0  4949.1    0.05       0  5030.1    0.05       0
  5239.2    0.12       0  5242.2    0.05       0  5349.7    0.12       0
  5476.6    0.05       0  5644.6    0.12       0
Bank Sta=4949.1,5030.1
Exp/Cntr=0.3,0.1

Type RM Length L Ch R = 1,218094,1531,1531,1531
BEGIN DESCRIPTION:
Mapping XS 4c3418bc
END DESCRIPTION:
XS GIS Cut Line= 2
      1672098.64      7020902.25      1674138.62      7020847.99
#Sta/Elev= 30
  3543.0 1459.87  4009.5 1442.17  4459.7 1429.35  4629.7 1416.44  4689.8 1414.41
  4719.8 1411.49  4849.8 1409.97  4877.8 1405.34  4899.8 1397.11  4919.8 1395.00
  4929.9 1391.92  4939.9 1383.83  4944.9 1382.22  4952.4 1381.22  5034.9 1382.22
  5041.8 1383.66  5059.9 1396.04  5089.9 1395.89  5099.9 1398.42  5149.9 1420.44
  5189.9 1441.30  5220.0 1452.21  5260.0 1470.41  5290.0 1481.84  5310.0 1494.56
  5340.0 1507.69  5360.0 1512.92  5380.0 1517.18  5410.0 1518.72  5583.7 1510.67
#Mann=5,-1,0
  3543.0    0.05       0  4877.8    0.12       0  4944.9    0.07       0
  5034.9    0.12       0  5041.8    0.05       0
Bank Sta=4944.9,5034.9
Exp/Cntr=0.3,0.1

Type RM Length L Ch R = 1,216563,1616,1616,1616
BEGIN DESCRIPTION:
Mapping XS 10f9685e
END DESCRIPTION:
XS GIS Cut Line= 2
      1671675.47      7021466.49      1673628.56      7022529.84
#Sta/Elev= 30
  3322.9 1470.30  3457.6 1460.53  3743.6 1447.68  4052.2 1436.81  4335.2 1430.22
  4760.7 1411.51  4848.1 1409.65  4893.6 1411.00  4907.9 1406.95  4929.7 1396.13
  4962.0 1394.60  4973.4 1386.31  4983.8 1382.21  4988.8 1382.21  4996.3 1381.21
  5078.8 1382.21  5093.1 1392.82  5121.4 1394.97  5136.7 1398.51  5144.1 1404.35
  5166.9 1413.31  5196.6 1433.27  5240.3 1450.59  5283.9 1470.98  5314.9 1482.70
  5349.5 1501.36  5381.8 1509.93  5425.5 1515.75  5507.1 1519.06  5546.7 1518.54
#Mann=3,-1,0
  3322.9    0.05       0  4988.8    0.03       0  5078.8    0.05       0
Bank Sta=4988.8,5078.8
Exp/Cntr=0.3,0.1

Type RM Length L Ch R = 1,214947,2602,2602,2602
BEGIN DESCRIPTION:
Mapping XS 791c2e2f
END DESCRIPTION:
XS GIS Cut Line= 2
      1671382.46      7022649.17      1672510.47      7023885.65
#Sta/Elev= 30
  3824.3 1440.51  3917.5 1435.71  3959.5 1437.31  4058.8 1435.27  4143.9 1429.94
  4405.4 1419.75  4433.8 1417.27  4448.0 1418.16  4624.2 1411.32  4738.5 1406.64
  4844.6 1407.84  4893.9 1405.97  4908.1 1402.50  4922.3 1396.47  4958.1 1393.55
  4972.4 1385.07  4982.4 1382.19  4990.7 1381.19  5081.4 1382.19  5085.1 1382.53
  5092.5 1389.22  5106.7 1393.33  5127.7 1394.80  5149.2 1401.29  5170.2 1412.04
  5205.4 1433.95  5227.0 1439.62  5304.7 1453.99  5396.6 1467.42  5498.0 1473.83
#Mann=5,-1,0
  3824.3    0.05       0  4624.2    0.12       0  4972.4    0.05       0
  4982.4    0.03       0  5081.4    0.05       0
Bank Sta=4982.4,5081.4
Exp/Cntr=0.3,0.1

Type RM Length L Ch R = 1,212345,1505,1505,1505
BEGIN DESCRIPTION:
Clear Fork Brazos Rv 55.0
END DESCRIPTION:
XS GIS Cut Line= 3
      1669905.03      7024938.00      1670405.00      7024938.00
      1671404.99      7025438.00
#Sta/Elev= 30
  4500.1 1465.10  4502.6 1465.10  4510.1 1459.36  4570.1 1438.45  4660.1 1418.85
  4690.1 1408.82  4760.1 1393.72  4800.1 1390.20  4880.1 1381.12  4950.1 1379.72
  4990.1 1380.16  4990.7 1376.97  4994.5 1375.97  5032.0 1375.97  5035.7 1376.97
  5053.2 1391.82  5058.8 1390.62  5075.5 1397.56  5089.5 1400.08  5156.6 1405.71
  5246.0 1407.08  5299.1 1406.20  5313.1 1404.99  5357.8 1405.13  5424.9 1400.49
  5469.6 1402.40  5559.1 1403.39  5637.5 1406.43  5785.2 1412.93  6118.1 1432.90
#Mann=5,-1,0
  4500.1    0.05       0  4990.7    0.05       0  5035.7    0.05       0
  5637.5    0.12       0  5785.2    0.05       0
Bank Sta=4990.7,5035.7
Exp/Cntr=0.3,0.1

Type RM Length L Ch R = 1,210840,1066,1066,1066
BEGIN DESCRIPTION:
Mapping XS b4af5982
END DESCRIPTION:
XS GIS Cut Line= 2
      1669657.28      7026316.75      1671545.28      7026544.61
#Sta/Elev= 30
  4296.4 1493.62  4354.5 1495.29  4415.0 1493.19  4485.5 1484.97  4518.1 1475.01
  4595.1 1442.36  4600.1 1443.00  4616.4 1435.87  4646.6 1429.46  4666.8 1420.32
  4682.2 1409.37  4687.2 1410.24  4727.2 1392.33  4777.6 1387.92  4851.2 1388.91
  4933.2 1386.47  4958.9 1381.26  4977.1 1373.87  4983.8 1372.87  5058.1 1373.87
  5097.3 1389.22  5102.3 1388.49  5140.2 1400.15  5191.2 1403.09  5251.0 1405.61
  5348.4 1414.76  5489.5 1418.24  5629.3 1421.41  5976.2 1431.15  6198.1 1432.59
#Mann=6,-1,0
  4296.4    0.05       0  4977.1    0.07       0  5058.1    0.05       0
  5191.2    0.05       0  5489.5    0.12       0  5629.3    0.05       0
Bank Sta=4977.1,5058.1
Exp/Cntr=0.3,0.1

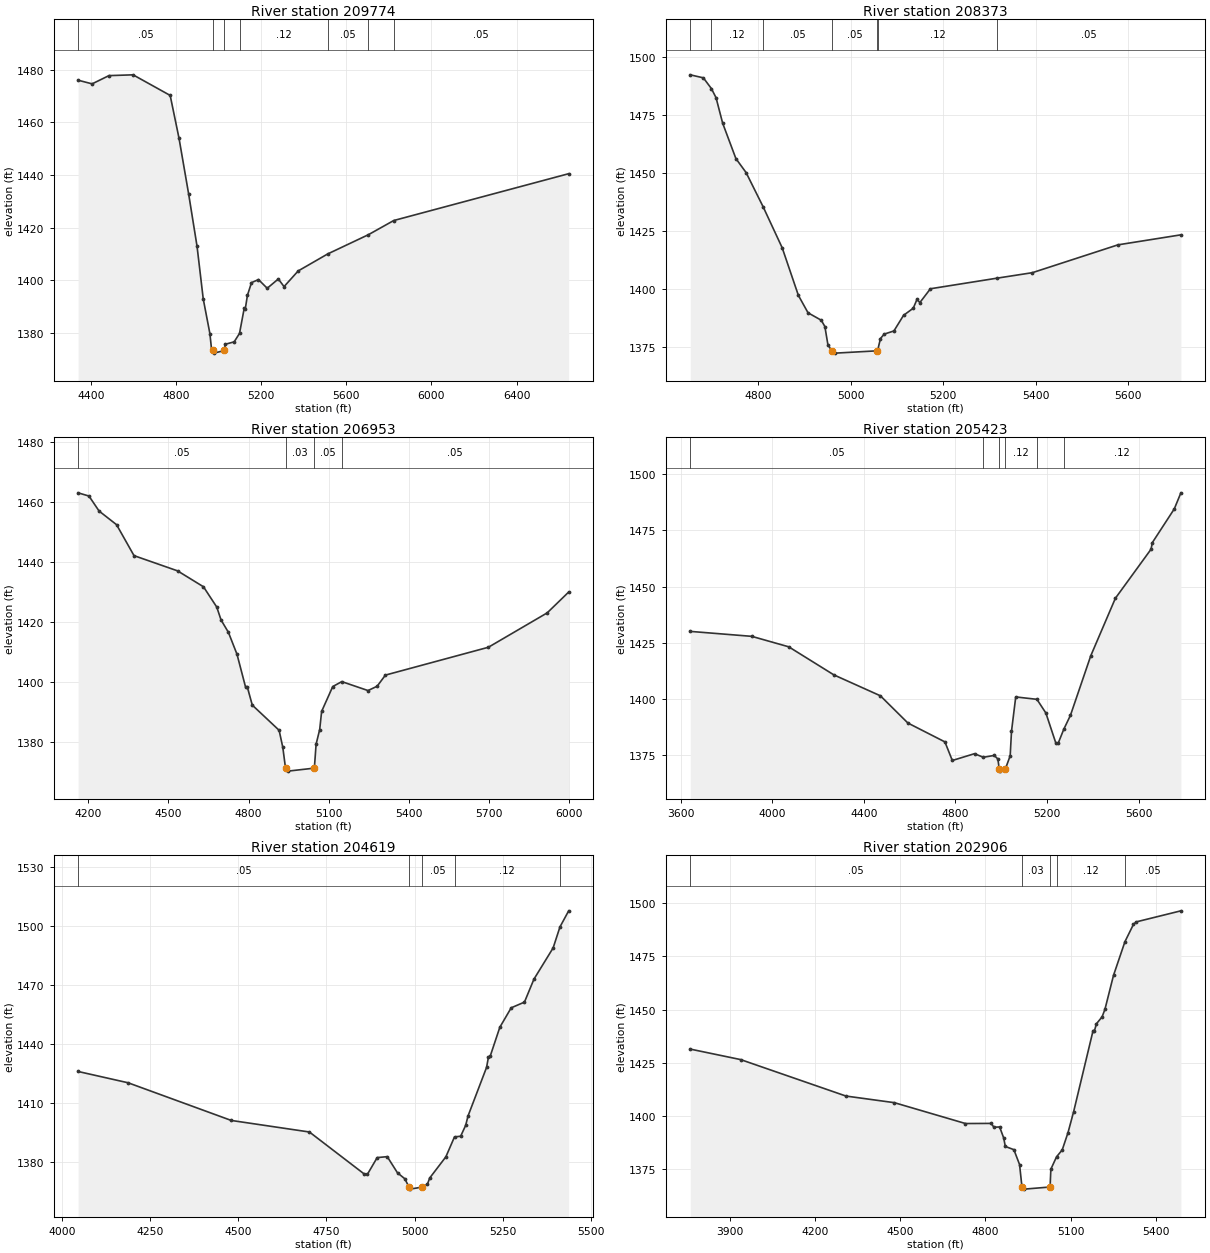
Type RM Length L Ch R = 1,209774,1401,1401,1401
BEGIN DESCRIPTION:
Mapping XS 99474b46
END DESCRIPTION:
XS GIS Cut Line= 2
      1669787.72      7027580.94      1672010.43      7026967.14
#Sta/Elev= 30
  4338.9 1475.98  4404.9 1474.59  4484.0 1477.72  4597.4 1478.02  4771.8 1470.20
  4813.3 1453.96  4858.5 1432.83  4898.1 1412.91  4927.2 1392.93  4958.5 1379.76
  4966.8 1373.35  4973.0 1373.35  4977.5 1372.35  5027.0 1373.35  5031.2 1375.73
  5072.6 1376.63  5097.7 1379.84  5119.7 1389.34  5124.9 1389.19  5134.9 1394.30
  5154.0 1399.11  5186.8 1400.28  5227.9 1396.98  5280.1 1400.50  5307.0 1397.61
  5373.5 1403.56  5511.9 1410.00  5703.8 1417.33  5822.6 1422.70  6644.8 1440.48
#Mann=7,-1,0
  4338.9    0.05       0  4973.0    0.05       0  5027.0    0.05       0
  5097.7    0.12       0  5511.9    0.05       0  5703.8    0.12       0
  5822.6    0.05       0
Bank Sta=4973,5027
Exp/Cntr=0.3,0.1

Type RM Length L Ch R = 1,208373,1420,1420,1420
BEGIN DESCRIPTION:
Clear Fork Brazos Rv 54.0
END DESCRIPTION:
XS GIS Cut Line= 3
      1671148.19      7028670.48      1671371.91      7028405.63
      1671805.01      7027837.98
#Sta/Elev= 30
  4653.3 1492.13  4681.6 1490.83  4699.0 1486.20  4709.0 1482.29  4723.3 1471.32
  4751.9 1456.09  4774.0 1450.05  4810.7 1435.37  4852.0 1417.69  4887.1 1397.15
  4907.9 1389.69  4936.5 1386.49  4944.3 1383.78  4950.8 1376.03  4958.9 1373.33
  4967.1 1372.33  5057.9 1373.33  5058.9 1373.92  5064.5 1378.61  5072.5 1380.51
  5093.6 1381.88  5114.4 1388.60  5135.4 1391.67  5143.4 1395.43  5149.7 1394.10
  5172.5 1400.04  5317.2 1404.62  5392.9 1406.96  5577.9 1418.94  5714.0 1423.25
#Mann=7,-1,0
  4653.3    0.05       0  4699.0    0.12       0  4810.7    0.05       0
  4958.9    0.05       0  5057.9    0.05       0  5058.9    0.12       0
  5317.2    0.05       0
Bank Sta=4958.9,5057.9
Exp/Cntr=0.3,0.1

Type RM Length L Ch R = 1,206953,1530,1530,1530
BEGIN DESCRIPTION:
Mapping XS b7c13d17
END DESCRIPTION:
XS GIS Cut Line= 3
      1671903.35      7029702.15      1672456.71      7029398.34
      1672782.24      7028237.29
#Sta/Elev= 30
  4161.5 1463.12  4202.3 1462.05  4240.2 1457.05  4305.6 1452.51  4371.0 1442.20
  4533.9 1437.14  4631.1 1431.83  4680.8 1425.08  4696.9 1420.78  4724.4 1416.67
  4756.6 1409.36  4788.9 1398.35  4795.5 1398.35  4813.9 1392.42  4914.3 1384.04
  4928.1 1378.37  4938.3 1371.44  4947.3 1370.44  5046.3 1371.44  5052.8 1379.40
  5066.3 1384.30  5073.5 1390.33  5115.1 1398.60  5149.0 1400.25  5247.2 1397.27
  5281.3 1398.71  5312.4 1402.42  5697.9 1411.69  5918.1 1423.14  5998.6 1430.08
#Mann=4,-1,0
  4161.5    0.05       0  4938.3    0.03       0  5046.3    0.05       0
  5149.0    0.05       0
Bank Sta=4938.3,5046.3
Exp/Cntr=0.3,0.1

Type RM Length L Ch R = 1,205423,804,804,804
BEGIN DESCRIPTION:
Mapping XS f671b1c3
END DESCRIPTION:
XS GIS Cut Line= 2
      1673368.93      7030920.32      1674168.25      7028931.32
#Sta/Elev= 30
  3641.4 1429.99  3910.2 1427.78  4071.5 1423.12  4269.0 1410.59  4472.0 1401.28
  4592.3 1389.13  4754.0 1380.72  4786.3 1372.43  4883.3 1375.47  4921.8 1373.86
  4969.5 1374.70  4985.4 1373.09  4991.3 1368.69  4993.6 1367.69  5018.3 1368.69
  5039.2 1374.55  5044.9 1385.41  5063.4 1400.77  5156.0 1399.70  5195.1 1393.60
  5238.9 1380.12  5248.8 1380.10  5273.2 1386.32  5302.6 1392.61  5391.3 1419.13
  5498.8 1444.76  5654.7 1466.64  5660.1 1469.55  5756.2 1484.61  5785.0 1491.77
#Mann=6,-1,0
  3641.4    0.05       0  4921.8    0.12       0  4991.3    0.07       0
  5018.3    0.12       0  5156.0    0.05       0  5273.2    0.12       0
Bank Sta=4991.3,5018.3
Exp/Cntr=0.3,0.1

Type RM Length L Ch R = 1,204619,1713,1713,1713
BEGIN DESCRIPTION:
Clear Fork Brazos Rv 53.0
END DESCRIPTION:
XS GIS Cut Line= 3
      1673648.60      7030759.91      1674405.00      7030188.00
      1674826.94      7030054.28
#Sta/Elev= 30
  4046.0 1426.19  4187.9 1420.45  4480.3 1401.33  4701.9 1395.46  4858.0 1374.04
  4866.3 1373.99  4894.0 1382.47  4922.5 1382.95  4951.6 1374.72  4972.4 1371.72
  4984.3 1367.46  4987.3 1366.46  5020.3 1367.46  5036.2 1368.81  5042.7 1372.06
  5088.7 1382.85  5113.2 1392.98  5130.6 1393.31  5144.8 1398.81  5151.6 1403.62
  5204.1 1428.26  5209.4 1433.48  5214.6 1434.06  5241.7 1448.63  5273.9 1458.51
  5311.5 1461.40  5338.5 1473.09  5392.9 1488.94  5412.2 1499.59  5436.9 1507.75
#Mann=5,-1,0
  4046.0    0.05       0  4984.3    0.05       0  5020.3    0.05       0
  5113.2    0.12       0  5412.2    0.05       0
Bank Sta=4984.3,5020.3
Exp/Cntr=0.3,0.1

Type RM Length L Ch R = 1,202906,2084,2084,2084
BEGIN DESCRIPTION:
Mapping XS f4a0c6d4
END DESCRIPTION:
XS GIS Cut Line= 2
      1673368.16      7031763.79      1675091.75      7031872.19
#Sta/Elev= 30
  3760.8 1431.47  3938.0 1426.55  4308.7 1409.43  4479.1 1406.32  4729.6 1396.52
  4819.7 1396.58  4829.7 1394.79  4849.8 1394.91  4864.1 1389.73  4869.8 1385.75
  4899.9 1384.25  4919.9 1377.27  4928.4 1366.72  4936.6 1365.72  5027.4 1366.72
  5030.1 1375.09  5050.1 1380.88  5070.2 1384.17  5090.3 1392.18  5110.3 1402.10
  5178.7 1440.15  5183.7 1440.14  5190.5 1443.35  5210.5 1446.63  5220.5 1450.16
  5250.6 1466.08  5290.9 1481.92  5320.7 1490.00  5330.7 1491.21  5487.8 1496.40
#Mann=5,-1,0
  3760.8    0.05       0  4928.4    0.03       0  5027.4    0.05       0
  5050.1    0.12       0  5290.9    0.05       0
Bank Sta=4928.4,5027.4
Exp/Cntr=0.3,0.1

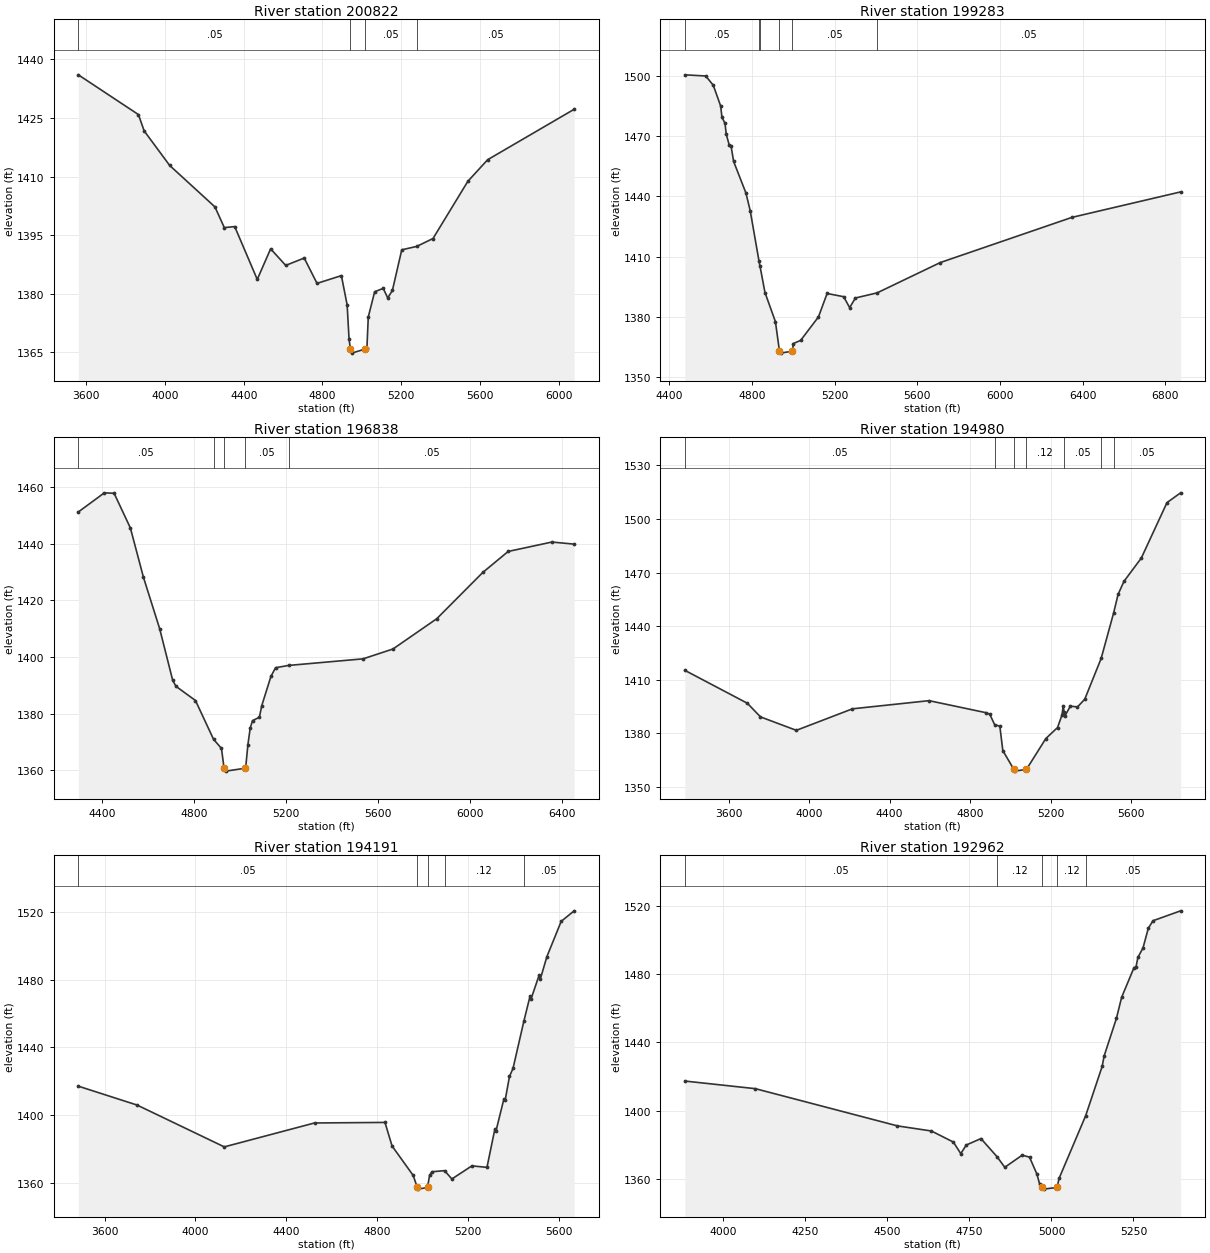
Type RM Length L Ch R = 1,200822,1539,1539,1539
BEGIN DESCRIPTION:
Mapping XS 7862bf2b
END DESCRIPTION:
XS GIS Cut Line= 2
      1672717.11      7033185.23      1675039.21      7034161.81
#Sta/Elev= 30
  3559.8 1436.07  3865.1 1425.88  3894.3 1421.69  4024.0 1412.83  4253.9 1402.21
  4301.4 1396.90  4354.3 1397.16  4468.8 1383.62  4536.8 1391.46  4613.4 1387.21
  4707.4 1389.10  4772.5 1382.60  4896.3 1384.59  4925.5 1377.09  4935.3 1368.26
  4942.4 1365.72  4948.4 1364.72  5014.4 1365.72  5025.9 1365.92  5032.9 1373.99
  5065.4 1380.46  5108.8 1381.32  5131.8 1378.87  5155.5 1380.80  5203.0 1391.21
  5279.2 1392.08  5361.7 1394.10  5538.8 1408.77  5639.2 1414.30  6078.9 1427.24
#Mann=4,-1,0
  3559.8    0.05       0  4942.4    0.07       0  5014.4    0.05       0
  5279.2    0.05       0
Bank Sta=4942.4,5014.4
Exp/Cntr=0.3,0.1

Type RM Length L Ch R = 1,199283,2445,2445,2445
BEGIN DESCRIPTION:
Mapping XS 05c569a5
END DESCRIPTION:
XS GIS Cut Line= 2
      1673672.02      7035485.56      1675635.99      7034107.52
#Sta/Elev= 30
  4474.5 1500.60  4575.9 1500.02  4612.3 1495.40  4648.1 1485.03  4654.2 1479.50
  4669.0 1476.44  4675.1 1471.05  4689.9 1465.46  4698.0 1465.32  4710.8 1457.43
  4770.1 1441.79  4791.0 1432.93  4833.8 1407.66  4838.7 1405.13  4862.5 1392.13
  4913.0 1377.64  4932.6 1362.96  4937.8 1361.96  4995.6 1362.96  4999.3 1366.71
  5035.0 1368.31  5121.3 1380.00  5163.1 1391.67  5243.3 1390.07  5272.2 1384.62
  5300.0 1389.42  5405.1 1391.98  5710.5 1407.07  6347.6 1429.58  6873.7 1442.28
#Mann=6,-1,0
  4474.5    0.05       0  4833.8    0.12       0  4838.7    0.05       0
  4932.6    0.07       0  4995.6    0.05       0  5405.1    0.05       0
Bank Sta=4932.6,4995.6
Exp/Cntr=0.3,0.1

Type RM Length L Ch R = 1,196838,1858,1858,1858
BEGIN DESCRIPTION:
Clear Fork Brazos Rv 51.0
END DESCRIPTION:
XS GIS Cut Line= 3
      1675754.98      7036338.02      1676255.00      7035838.00
      1676326.85      7034391.42
#Sta/Elev= 30
  4298.2 1451.31  4411.4 1458.08  4453.8 1457.92  4524.5 1445.64  4581.1 1428.25
  4651.8 1410.00  4708.4 1391.78  4722.5 1389.64  4807.4 1384.61  4885.9 1370.92
  4920.5 1367.65  4931.8 1360.63  4939.3 1359.63  5021.8 1360.63  5025.4 1360.63
  5035.4 1369.01  5045.4 1374.86  5055.4 1377.49  5085.4 1378.69  5095.5 1382.77
  5135.5 1393.13  5155.5 1396.21  5212.1 1397.02  5536.0 1399.35  5666.2 1402.84
  5856.4 1413.55  6056.6 1429.92  6166.8 1437.34  6357.0 1440.67  6453.7 1439.93
#Mann=5,-1,0
  4298.2    0.05       0  4885.9    0.12       0  4931.8    0.03       0
  5021.8    0.05       0  5212.1    0.05       0
Bank Sta=4931.8,5021.8
Exp/Cntr=0.3,0.1

Type RM Length L Ch R = 1,194980,789,789,789
BEGIN DESCRIPTION:
Mapping XS 67f5a726
END DESCRIPTION:
XS GIS Cut Line= 2
      1676666.77      7036863.63      1678672.95      7035432.19
#Sta/Elev= 30
  3381.7 1415.31  3692.7 1396.88  3757.9 1389.25  3936.1 1381.73  4215.1 1393.77
  4595.7 1398.33  4876.4 1391.66  4897.3 1390.80  4921.4 1384.98  4947.7 1384.00
  4962.4 1370.42  5017.0 1359.91  5022.3 1358.91  5080.0 1359.91  5176.3 1377.15
  5234.5 1383.30  5256.2 1390.20  5262.3 1395.08  5267.1 1392.10  5270.9 1389.74
  5298.0 1395.26  5333.6 1394.83  5369.6 1399.12  5451.2 1421.95  5513.6 1447.56
  5535.2 1457.75  5564.7 1465.10  5650.7 1478.09  5778.5 1509.14  5846.2 1514.60
#Mann=7,-1,0
  3381.7    0.05       0  4921.4    0.12       0  5017.0    0.07       0
  5080.0    0.12       0  5267.1    0.05       0  5451.2    0.12       0
  5513.6    0.05       0
Bank Sta=5017,5080
Exp/Cntr=0.3,0.1

Type RM Length L Ch R = 1,194191,1229,1229,1229
BEGIN DESCRIPTION:
Mapping XS b3b1d5fa
END DESCRIPTION:
XS GIS Cut Line= 2
      1676689.70      7037050.18      1678800.23      7036483.04
#Sta/Elev= 30
  3483.6 1417.02  3742.6 1405.85  4126.9 1381.12  4524.6 1395.26  4835.2 1395.58
  4866.3 1381.68  4959.5 1364.23  4977.6 1357.14  4981.3 1356.14  5022.6 1357.14
  5031.9 1364.35  5042.3 1366.42  5097.7 1367.07  5130.0 1362.14  5218.3 1369.90
  5284.7 1369.01  5319.5 1391.63  5324.7 1390.69  5359.5 1409.55  5364.7 1408.58
  5384.0 1422.82  5399.5 1427.49  5447.4 1455.49  5474.2 1470.05  5479.4 1468.75
  5514.2 1482.48  5519.4 1480.15  5549.0 1493.67  5611.8 1514.46  5669.0 1520.70
#Mann=5,-1,0
  3483.6    0.05       0  4977.6    0.03       0  5022.6    0.05       0
  5097.7    0.12       0  5447.4    0.05       0
Bank Sta=4977.6,5022.6
Exp/Cntr=0.3,0.1

Type RM Length L Ch R = 1,192962,1321,1321,1321
BEGIN DESCRIPTION:
Clear Fork Brazos Rv 50.0
END DESCRIPTION:
XS GIS Cut Line= 3
      1676655.03      7037138.02      1677655.00      7037638.00
      1677998.69      7037829.62
#Sta/Elev= 30
  3882.2 1417.27  4097.4 1412.80  4530.6 1391.00  4634.0 1388.02  4701.1 1381.52
  4723.5 1374.76  4740.3 1379.81  4785.0 1383.58  4834.2 1372.93  4857.6 1366.77
  4910.8 1373.87  4933.1 1372.70  4955.5 1362.83  4963.9 1356.94  4972.3 1354.98
  4976.0 1353.98  5017.3 1354.98  5023.1 1360.24  5104.2 1396.95  5154.5 1425.83
  5160.5 1431.93  5197.9 1453.90  5213.9 1466.32  5251.6 1483.67  5257.3 1483.78
  5263.5 1489.66  5279.1 1495.27  5295.1 1506.65  5309.3 1511.12  5393.7 1516.94
#Mann=5,-1,0
  3882.2    0.05       0  4834.2    0.12       0  4972.3    0.07       0
  5017.3    0.12       0  5104.2    0.05       0
Bank Sta=4972.3,5017.3
Exp/Cntr=0.3,0.1

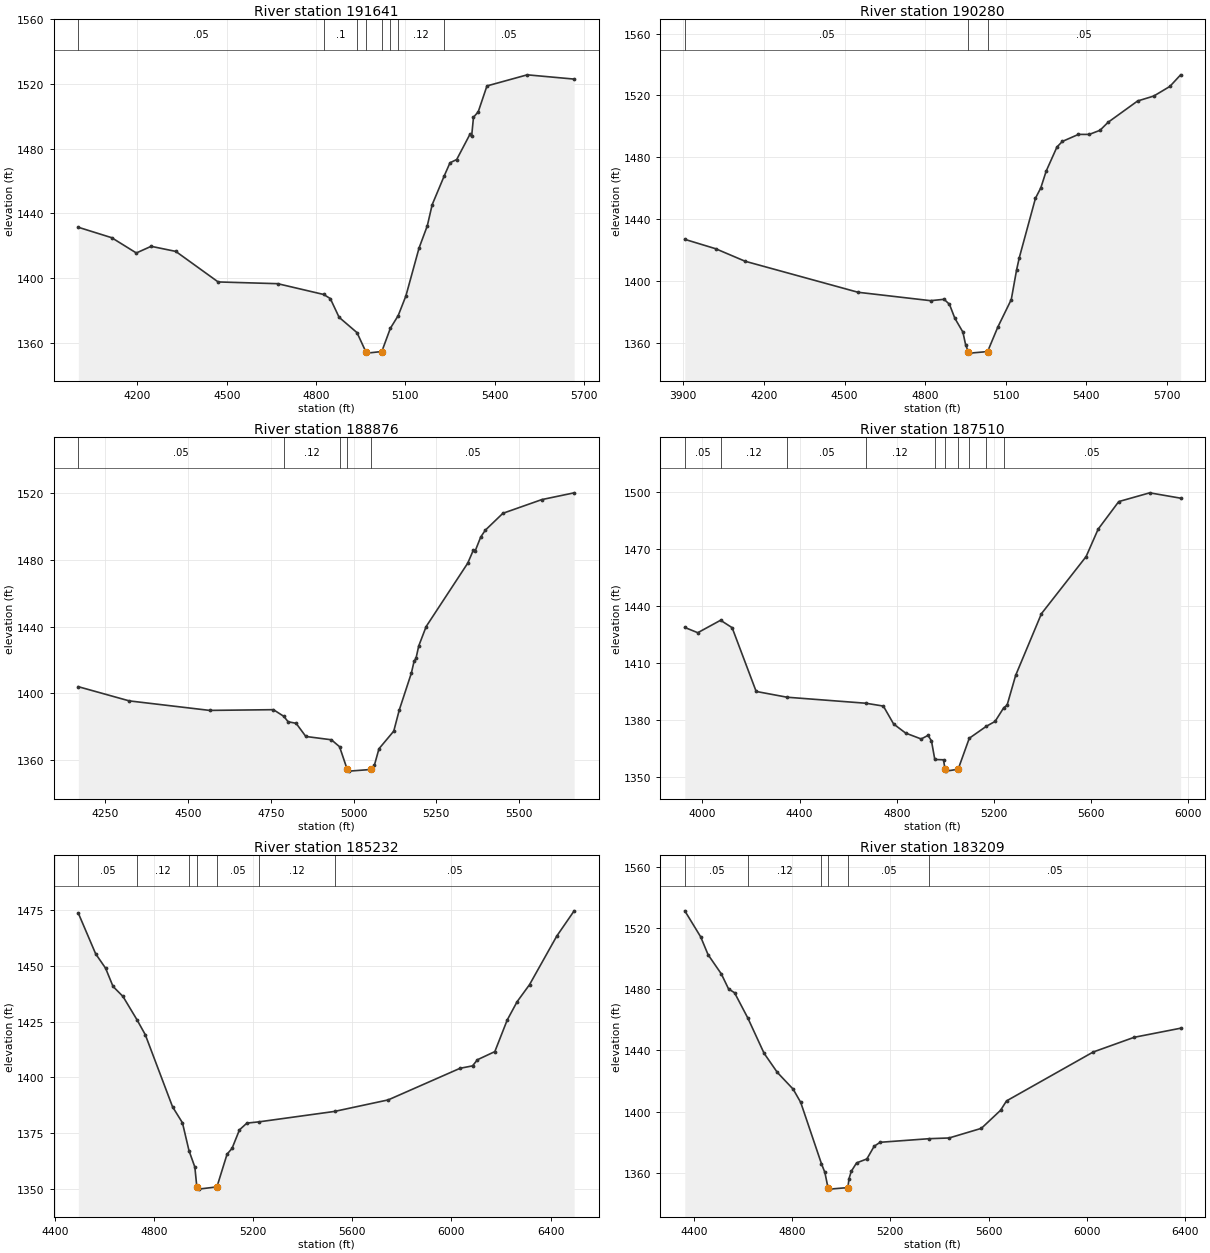
Type RM Length L Ch R = 1,191641,1361,1361,1361
BEGIN DESCRIPTION:
Mapping XS 57b9d001
END DESCRIPTION:
XS GIS Cut Line= 2
      1676059.13      7037351.89      1676829.54      7038827.59
#Sta/Elev= 30
  4001.9 1431.35  4113.9 1424.90  4196.6 1415.45  4246.4 1419.57  4329.1 1416.42
  4471.3 1397.54  4671.2 1396.46  4825.7 1389.78  4847.9 1387.25  4877.4 1375.68
  4937.6 1366.17  4966.8 1354.51  4971.3 1353.51  5020.8 1354.51  5049.5 1368.86
  5075.8 1376.71  5101.6 1388.85  5145.8 1418.49  5173.5 1432.23  5189.9 1445.31
  5230.7 1463.26  5249.7 1471.22  5272.2 1473.24  5316.8 1488.89  5322.4 1487.64
  5328.6 1499.38  5344.5 1502.75  5373.8 1518.76  5509.1 1525.63  5666.6 1522.99
#Mann=8,-1,0
  4001.9    0.05       0  4825.7     0.1       0  4937.6    0.12       0
  4966.8    0.07       0  5020.8    0.12       0  5049.5    0.05       0
  5075.8    0.12       0  5230.7    0.05       0
Bank Sta=4966.8,5020.8
Exp/Cntr=0.3,0.1

Type RM Length L Ch R = 1,190280,1404,1404,1404
BEGIN DESCRIPTION:
Mapping XS 57ac023c
END DESCRIPTION:
XS GIS Cut Line= 2
      1675201.94      7037243.35      1675180.23      7039088.03
#Sta/Elev= 30
  3905.8 1426.92  4020.5 1420.86  4130.5 1412.74  4550.5 1392.69  4820.5 1387.26
  4870.5 1388.15  4890.5 1384.91  4910.5 1375.91  4940.5 1366.95  4950.5 1358.89
  4960.4 1354.34  4966.4 1353.34  5032.4 1354.34  5070.5 1370.21  5120.5 1387.99
  5140.5 1407.35  5150.5 1415.16  5210.5 1453.49  5230.5 1460.26  5250.5 1471.10
  5290.5 1486.65  5310.5 1490.23  5370.5 1494.79  5410.6 1494.78  5450.6 1497.44
  5480.6 1502.60  5590.6 1516.40  5650.6 1519.58  5710.6 1525.81  5750.6 1533.31
#Mann=3,-1,0
  3905.8    0.05       0  4960.4    0.03       0  5032.4    0.05       0
Bank Sta=4960.4,5032.4
Exp/Cntr=0.3,0.1

Type RM Length L Ch R = 1,188876,1366,1366,1366
BEGIN DESCRIPTION:
Clear Fork Brazos Rv 49.0
END DESCRIPTION:
XS GIS Cut Line= 3
      1674169.29      7037322.67      1673855.00      7038088.00
      1673554.99      7038688.03
#Sta/Elev= 30
  4168.4 1403.99  4322.3 1395.47  4565.1 1389.76  4757.9 1390.19  4789.1 1386.22
  4802.4 1382.93  4826.4 1382.02  4855.8 1374.11  4933.1 1372.12  4957.7 1367.96
  4980.9 1354.30  4986.9 1353.30  5052.9 1354.30  5062.8 1356.70  5076.8 1366.74
  5121.5 1377.32  5138.3 1390.10  5174.6 1412.09  5183.0 1419.31  5188.6 1420.93
  5197.0 1428.48  5219.4 1440.11  5345.1 1478.18  5361.9 1485.94  5367.5 1485.47
  5384.3 1493.87  5398.2 1497.97  5451.3 1508.10  5568.7 1516.32  5666.6 1520.39
#Mann=5,-1,0
  4168.4    0.05       0  4789.1    0.12       0  4957.7    0.05       0
  4980.9    0.03       0  5052.9    0.05       0
Bank Sta=4980.9,5052.9
Exp/Cntr=0.3,0.1

Type RM Length L Ch R = 1,187510,2278,2278,2278
BEGIN DESCRIPTION:
Mapping XS 266ea7f7
END DESCRIPTION:
XS GIS Cut Line= 2
      1673454.95      7036722.59      1671990.64      7038143.51
#Sta/Elev= 30
  3927.8 1428.65  3981.2 1425.89  4075.1 1432.43  4122.6 1428.52  4221.5 1395.04
  4348.5 1392.01  4672.9 1388.85  4744.9 1387.36  4787.3 1377.92  4836.7 1373.17
  4900.5 1370.08  4928.8 1371.97  4942.9 1369.07  4956.6 1359.30  4992.4 1359.15
  4998.7 1354.19  5003.2 1353.19  5052.7 1354.19  5098.5 1370.46  5168.8 1376.75
  5204.6 1379.30  5240.4 1386.50  5254.0 1387.81  5289.4 1403.52  5395.4 1435.88
  5579.3 1465.89  5628.8 1480.28  5713.6 1494.76  5841.0 1499.36  5968.2 1496.55
#Mann=10,-1,0
  3927.8    0.05       0  4075.1    0.12       0  4348.5    0.05       0
  4672.9    0.12       0  4956.6    0.05       0  4998.7    0.05       0
  5052.7    0.05       0  5098.5    0.05       0  5168.8    0.12       0
  5240.4    0.05       0
Bank Sta=4998.7,5052.7
Exp/Cntr=0.3,0.1

Type RM Length L Ch R = 1,185232,2023,2023,2023
BEGIN DESCRIPTION:
Clear Fork Brazos Rv 48.0
END DESCRIPTION:
XS GIS Cut Line= 3
      1671105.00      7035438.01      1671105.00      7035938.00
      1671105.00      7037438.01
#Sta/Elev= 30
  4494.9 1473.58  4564.9 1455.35  4604.9 1448.91  4634.9 1440.75  4674.9 1436.28
  4731.9 1425.74  4764.9 1419.15  4874.9 1386.83  4914.9 1379.65  4941.3 1367.16
  4964.9 1359.81  4972.9 1350.93  4979.7 1349.93  5053.9 1350.93  5094.9 1365.61
  5114.9 1368.19  5144.9 1376.50  5174.9 1379.52  5223.7 1380.08  5528.3 1384.75
  5744.9 1389.92  6034.9 1404.09  6084.9 1405.16  6104.9 1407.92  6174.9 1411.55
  6224.9 1425.72  6264.9 1433.94  6314.9 1441.56  6424.9 1463.35  6494.9 1474.64
#Mann=7,-1,0
  4494.9    0.05       0  4731.9    0.12       0  4941.3    0.05       0
  4972.9    0.03       0  5053.9    0.05       0  5223.7    0.12       0
  5528.3    0.05       0
Bank Sta=4972.9,5053.9
Exp/Cntr=0.3,0.1

Type RM Length L Ch R = 1,183209,1834,1834,1834
BEGIN DESCRIPTION:
Mapping XS 3d6d4884
END DESCRIPTION:
XS GIS Cut Line= 2
      1668973.65      7035387.95      1669721.91      7037264.03
#Sta/Elev= 30
  4362.8 1531.20  4427.5 1514.20  4457.6 1502.56  4511.6 1489.98  4541.2 1480.14
  4565.5 1477.68  4619.9 1461.05  4685.8 1438.12  4739.7 1425.64  4804.3 1414.68
  4835.0 1406.04  4919.6 1365.92  4933.5 1360.26  4946.0 1350.38  4952.8 1349.38
  5027.0 1350.38  5031.8 1356.25  5041.1 1361.05  5062.6 1366.52  5104.5 1369.10
  5134.2 1377.39  5158.5 1379.98  5358.8 1382.34  5439.5 1382.80  5570.8 1389.09
  5649.0 1400.86  5673.3 1407.01  6026.4 1438.96  6193.5 1448.58  6382.6 1454.51
#Mann=6,-1,0
  4362.8    0.05       0  4619.9    0.12       0  4919.6    0.05       0
  4946.0    0.03       0  5027.0    0.05       0  5358.8    0.05       0
Bank Sta=4946,5027
Exp/Cntr=0.3,0.1

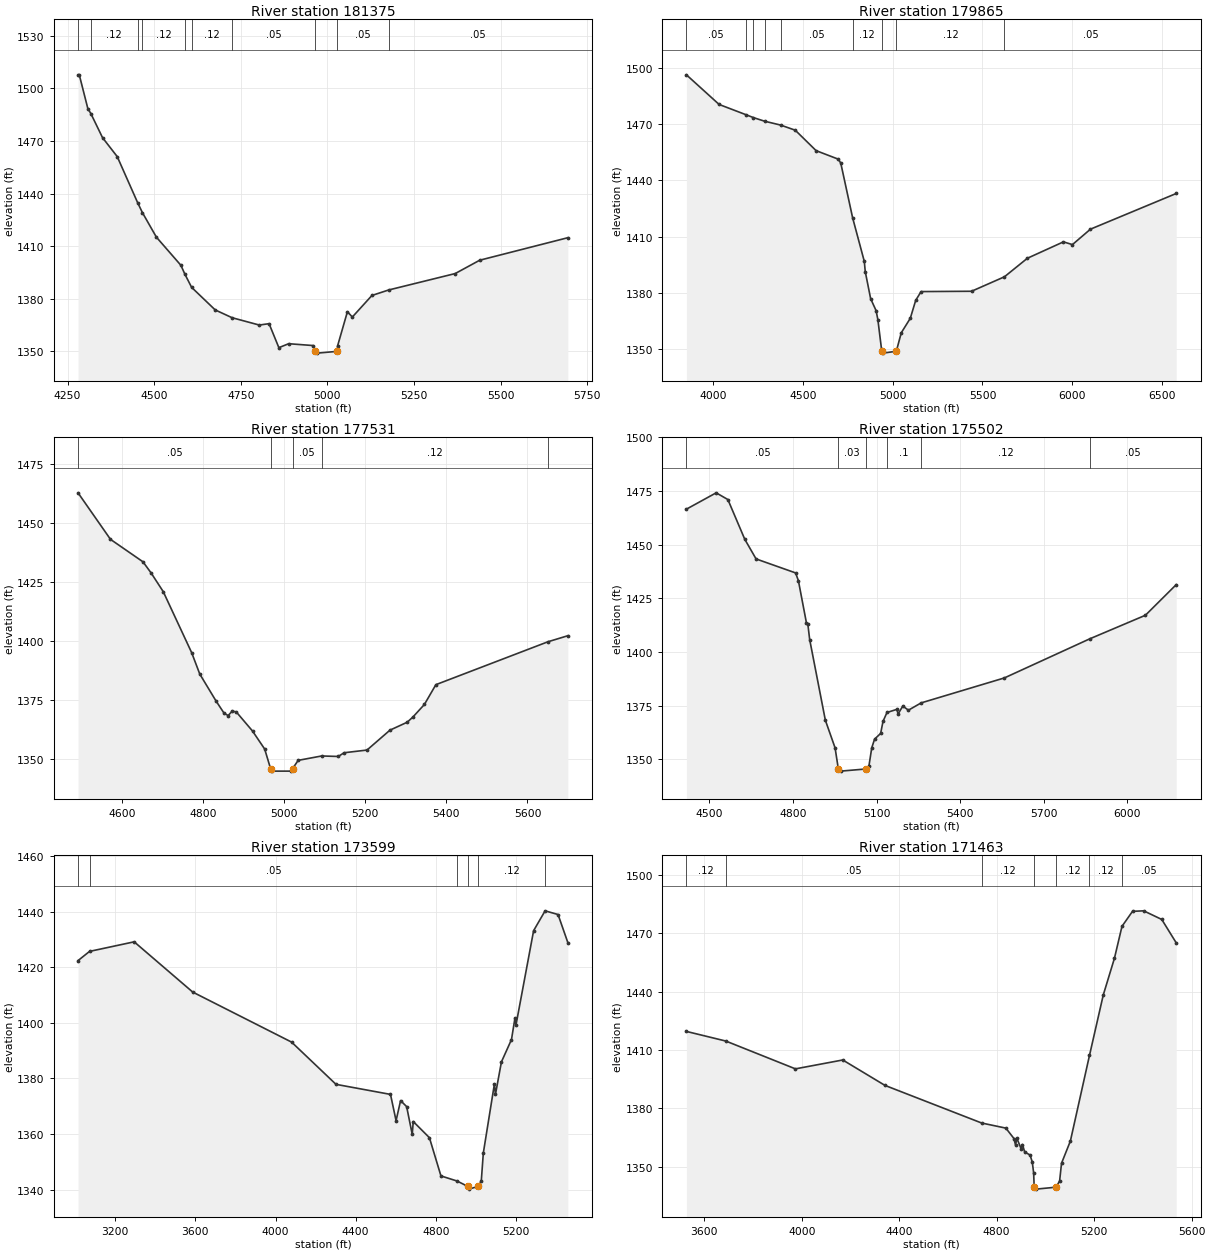
Type RM Length L Ch R = 1,181375,1510,1510,1510
BEGIN DESCRIPTION:
Clear Fork Brazos Rv 47.0
END DESCRIPTION:
XS GIS Cut Line= 3
      1667654.98      7036837.98      1668155.00      7037338.00
      1668654.97      7037837.97
#Sta/Elev= 30
  4280.1 1507.72  4283.7 1507.72  4308.4 1488.50  4317.2 1485.61  4350.8 1471.91
  4393.3 1461.09  4452.2 1434.84  4465.9 1429.20  4506.4 1415.17  4577.1 1399.13
  4588.5 1394.12  4608.1 1386.55  4676.1 1373.70  4724.9 1369.25  4803.4 1365.07
  4831.7 1365.85  4860.0 1352.17  4888.2 1354.43  4959.0 1353.38  4965.4 1350.06
  4970.6 1349.06  5028.4 1350.06  5029.7 1353.30  5057.9 1372.68  5072.1 1369.63
  5128.7 1381.94  5176.8 1385.05  5369.1 1394.42  5439.8 1402.02  5694.3 1414.86
#Mann=10,-1,0
  4280.1    0.05       0  4317.2    0.12       0  4452.2    0.05       0
  4465.9    0.12       0  4588.5    0.05       0  4608.1    0.12       0
  4724.9    0.05       0  4965.4    0.07       0  5028.4    0.05       0
  5176.8    0.05       0
Bank Sta=4965.4,5028.4
Exp/Cntr=0.3,0.1

Type RM Length L Ch R = 1,179865,2334,2334,2334
BEGIN DESCRIPTION:
Mapping XS 675d601a
END DESCRIPTION:
XS GIS Cut Line= 3
      1666488.82      7038100.59      1667085.62      7038512.92
      1669081.06      7038664.75
#Sta/Elev= 30
  3852.0 1496.30  4034.0 1480.51  4182.6 1475.08  4224.8 1473.51  4286.8 1471.59
  4376.5 1469.52  4457.8 1466.79  4574.0 1455.89  4697.1 1451.37  4711.2 1449.28
  4777.3 1420.08  4842.3 1396.85  4847.5 1391.45  4877.6 1376.97  4907.7 1370.69
  4917.8 1365.81  4939.5 1348.99  4946.3 1347.99  5020.5 1348.99  5048.1 1358.84
  5098.3 1366.56  5128.4 1376.13  5158.4 1380.79  5439.3 1380.96  5622.4 1388.67
  5750.1 1398.55  5950.7 1407.28  6000.9 1405.83  6101.2 1414.05  6578.6 1433.06
#Mann=9,-1,0
  3852.0    0.05       0  4182.6    0.12       0  4224.8    0.05       0
  4286.8    0.12       0  4376.5    0.05       0  4777.3    0.12       0
  4939.5    0.07       0  5020.5    0.12       0  5622.4    0.05       0
Bank Sta=4939.5,5020.5
Exp/Cntr=0.3,0.1

Type RM Length L Ch R = 1,177531,2029,2029,2029
BEGIN DESCRIPTION:
Clear Fork Brazos Rv 46.0
END DESCRIPTION:
XS GIS Cut Line= 3
      1668004.96      7040388.00      1668505.00      7040388.00
      1669004.97      7039888.03
#Sta/Elev= 30
  4492.3 1462.61  4572.3 1442.90  4652.3 1433.40  4672.3 1428.70  4702.3 1420.76
  4772.3 1394.93  4792.3 1385.86  4832.3 1374.47  4852.3 1369.25  4862.3 1368.27
  4872.3 1370.16  4882.3 1369.81  4922.3 1361.72  4952.3 1354.08  4966.9 1345.73
  4971.4 1344.73  5016.4 1344.73  5020.9 1345.73  5034.8 1349.29  5092.7 1351.15
  5133.8 1350.94  5147.9 1352.51  5204.5 1353.66  5261.0 1362.08  5303.5 1365.44
  5317.6 1367.64  5345.9 1372.96  5374.2 1381.35  5650.5 1399.53  5699.4 1402.08
#Mann=5,-1,0
  4492.3    0.05       0  4966.9    0.05       0  5020.9    0.05       0
  5092.7    0.12       0  5650.5    0.05       0
Bank Sta=4966.9,5020.9
Exp/Cntr=0.3,0.1

Type RM Length L Ch R = 1,175502,1903,1903,1903
BEGIN DESCRIPTION:
Mapping XS ea740ddf
END DESCRIPTION:
XS GIS Cut Line= 2
      1670112.97      7041854.89      1670384.22      7040118.85
#Sta/Elev= 30
  4417.7 1466.58  4524.4 1474.19  4566.4 1471.06  4627.1 1452.53  4667.6 1443.39
  4809.3 1436.88  4819.4 1433.27  4848.3 1413.56  4853.4 1412.87  4859.9 1405.80
  4916.1 1368.25  4951.0 1355.37  4962.7 1345.53  4971.0 1344.53  5061.7 1345.53
  5072.4 1346.88  5082.6 1355.41  5092.7 1359.43  5114.5 1362.11  5123.0 1367.73
  5137.2 1371.85  5172.2 1373.29  5177.3 1371.20  5193.9 1374.85  5214.1 1372.93
  5259.8 1376.32  5558.3 1387.95  5864.7 1406.17  6064.3 1417.15  6174.8 1431.41
#Mann=6,-1,0
  4417.7    0.05       0  4962.7    0.03       0  5061.7    0.05       0
  5137.2     0.1       0  5259.8    0.12       0  5864.7    0.05       0
Bank Sta=4962.7,5061.7
Exp/Cntr=0.3,0.1

Type RM Length L Ch R = 1,173599,2136,2136,2136
BEGIN DESCRIPTION:
Clear Fork Brazos Rv 45.0
END DESCRIPTION:
XS GIS Cut Line= 3
      1671703.09      7043166.20      1671948.94      7041195.48
      1671905.00      7040737.99
#Sta/Elev= 30
  3014.0 1422.36  3071.6 1425.67  3294.4 1429.11  3586.6 1411.05  4080.4 1393.06
  4302.1 1377.88  4574.2 1374.27  4602.0 1364.83  4624.6 1372.04  4654.8 1369.88
  4682.7 1359.91  4687.8 1364.52  4768.5 1358.71  4826.1 1344.97  4907.0 1343.12
  4959.4 1341.22  4963.9 1340.22  5013.4 1341.22  5027.6 1343.22  5037.7 1353.20
  5093.2 1378.07  5098.2 1374.24  5128.1 1385.95  5178.3 1393.98  5195.7 1401.74
  5200.8 1399.22  5288.8 1433.12  5346.2 1440.25  5410.8 1438.92  5459.6 1428.86
#Mann=6,-1,0
  3014.0    0.12       0  3071.6    0.05       0  4907.0    0.12       0
  4959.4    0.07       0  5013.4    0.12       0  5346.2    0.05       0
Bank Sta=4959.4,5013.4
Exp/Cntr=0.3,0.1

Type RM Length L Ch R = 1,171463,2117,2117,2117
BEGIN DESCRIPTION:
Mapping XS 4326c42a
END DESCRIPTION:
XS GIS Cut Line= 2
      1672066.05      7043222.14      1673888.96      7042375.79
#Sta/Elev= 30
  3526.9 1419.53  3688.6 1414.59  3974.2 1400.31  4168.4 1404.87  4341.6 1391.82
  4738.2 1372.51  4837.7 1369.88  4870.8 1364.55  4877.4 1361.20  4882.9 1364.67
  4900.3 1359.27  4905.8 1361.47  4914.9 1357.63  4937.0 1356.07  4946.1 1352.47
  4951.6 1346.94  4954.0 1339.56  4961.5 1338.56  5044.0 1339.56  5058.3 1342.80
  5066.1 1351.84  5102.4 1363.23  5180.8 1407.20  5237.4 1438.25  5283.2 1457.08
  5314.2 1473.49  5357.4 1481.19  5403.2 1481.45  5477.4 1477.02  5536.7 1465.02
#Mann=7,-1,0
  3526.9    0.12       0  3688.6    0.05       0  4738.2    0.12       0
  4954.0    0.07       0  5044.0    0.12       0  5180.8    0.12       0
  5314.2    0.05       0
Bank Sta=4954,5044
Exp/Cntr=0.3,0.1