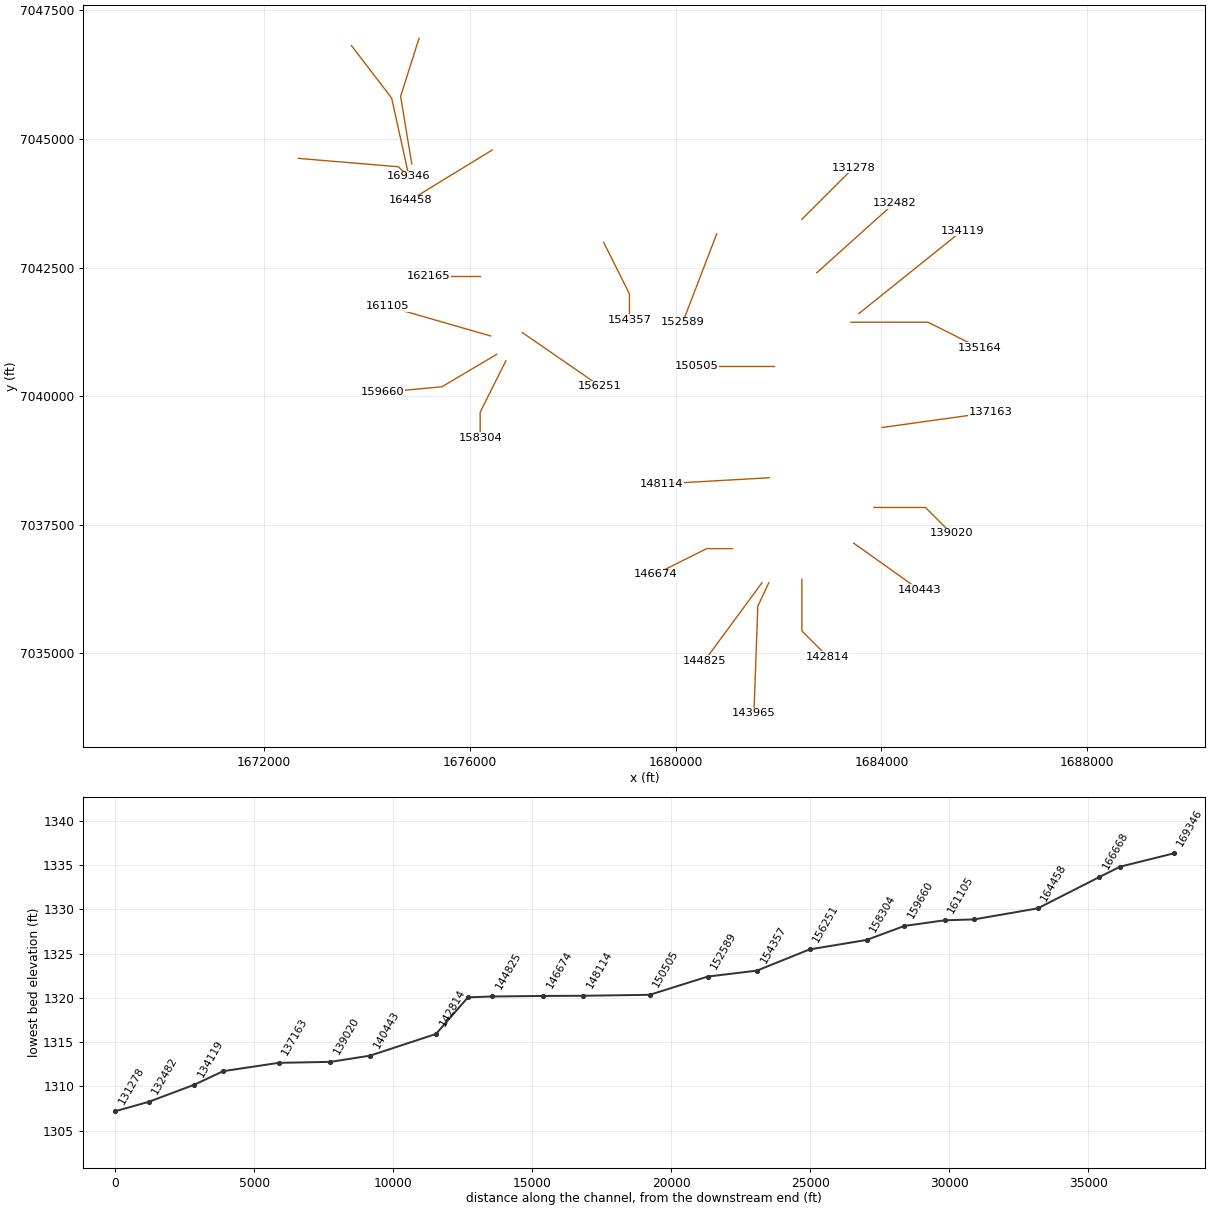
HEC-RAS study Clear Fork Brazos Rv.prj: Clear Fork Brazos Rv Base Level Engineering

--- Clear Fork Brazos Rv.g01 (geometry) --- (continued)

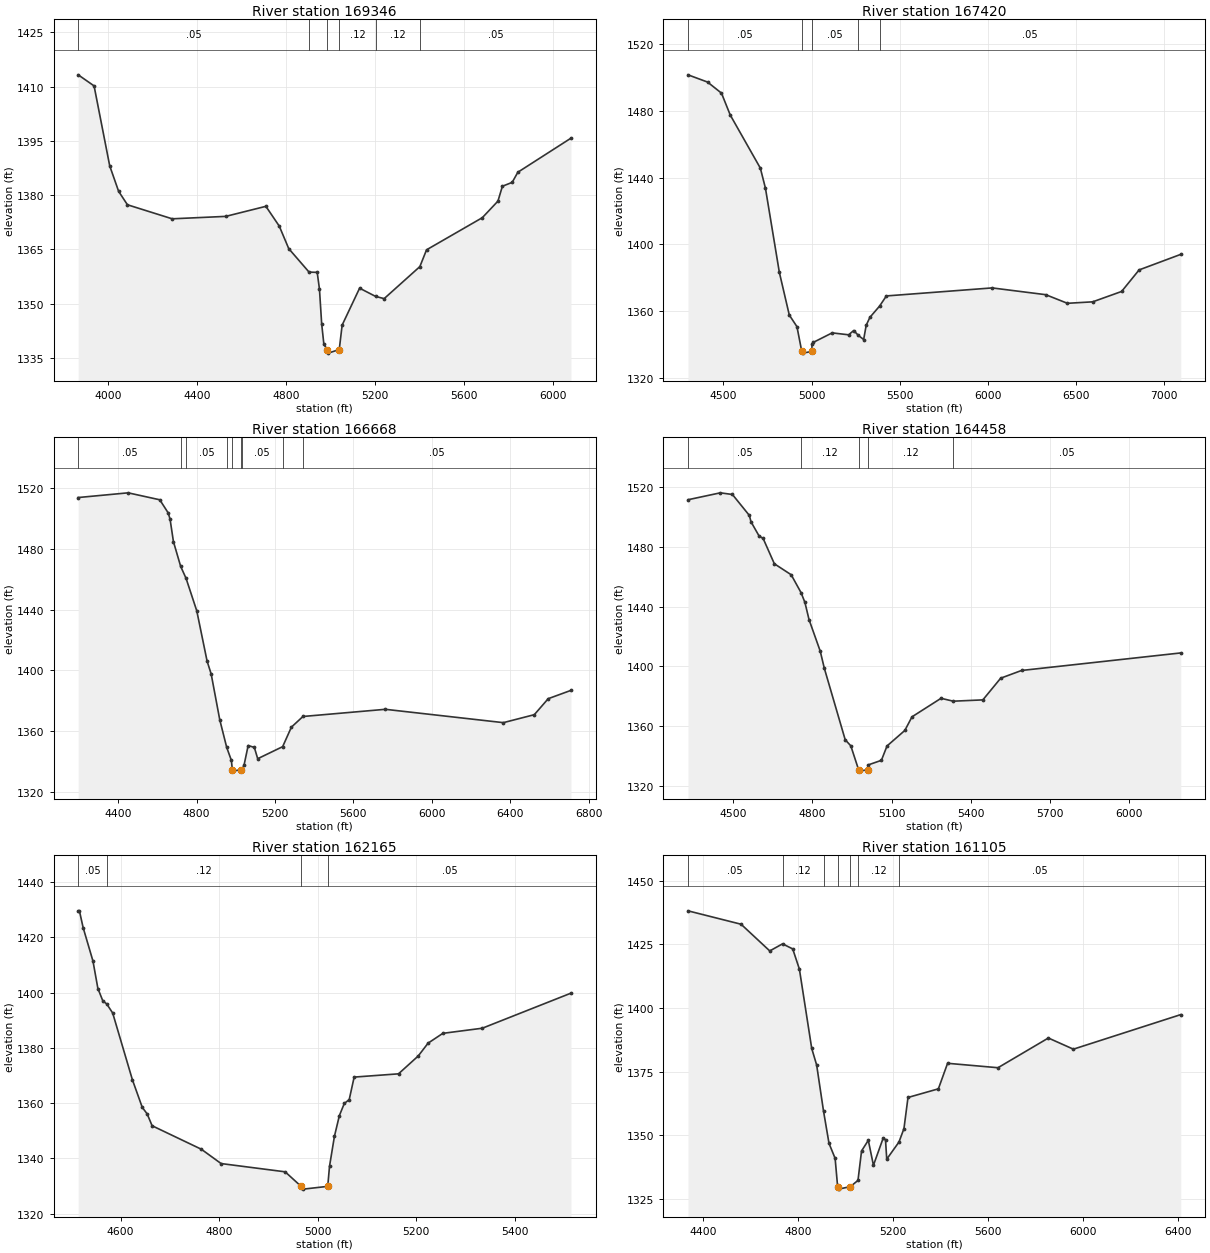
Type RM Length L Ch R = 1,169346,1926,1926,1926
BEGIN DESCRIPTION:
Mapping XS e6c45d98
END DESCRIPTION:
XS GIS Cut Line= 3
      1672673.72      7044621.86      1674616.00      7044459.10
      1674806.78      7044271.87
#Sta/Elev= 30
  3865.0 1413.24  3936.5 1410.18  4006.8 1388.09  4046.9 1381.04  4086.5 1377.33
  4287.8 1373.45  4528.6 1374.12  4709.2 1376.90  4769.4 1371.43  4812.0 1365.21
  4903.4 1358.72  4940.0 1358.65  4950.1 1354.06  4960.1 1344.42  4970.1 1338.72
  4985.2 1337.33  4989.7 1336.33  5039.2 1337.33  5052.2 1344.08  5130.7 1354.28
  5202.4 1352.01  5241.1 1351.39  5401.7 1360.24  5431.8 1364.88  5682.6 1373.76
  5752.9 1378.34  5772.9 1382.45  5816.9 1383.52  5842.4 1386.32  6081.4 1395.74
#Mann=6,-1,0
  3865.0    0.05       0  4903.4    0.12       0  4985.2    0.07       0
  5039.2    0.12       0  5202.4    0.12       0  5401.7    0.05       0
Bank Sta=4985.2,5039.2
Exp/Cntr=0.3,0.1

Type RM Length L Ch R = 1,167420,752,752,752
BEGIN DESCRIPTION:
Mapping XS 64f6fdea
END DESCRIPTION:
XS GIS Cut Line= 4
      1673704.51      7046813.74      1674485.79      7045793.74
      1674767.91      7044513.36      1674810.42      7044320.41
#Sta/Elev= 30
  4299.6 1501.78  4410.6 1497.44  4489.5 1490.80  4539.4 1477.63  4709.9 1445.81
  4738.8 1433.75  4817.7 1383.23  4873.9 1357.70  4917.4 1350.70  4944.7 1335.83
  4949.2 1334.83  5002.0 1335.83  5002.6 1340.10  5010.9 1341.32  5116.9 1346.98
  5210.3 1345.82  5239.0 1348.38  5265.3 1345.48  5295.5 1342.99  5310.0 1351.57
  5330.8 1356.28  5386.1 1363.09  5424.3 1369.14  6023.9 1373.95  6327.6 1369.89
  6450.5 1364.72  6593.8 1365.60  6757.7 1371.82  6856.9 1384.75  7093.1 1394.08
#Mann=5,-1,0
  4299.6    0.05       0  4944.7    0.05       0  5002.0    0.05       0
  5265.3    0.12       0  5386.1    0.05       0
Bank Sta=4944.7,5002
Exp/Cntr=0.3,0.1

Type RM Length L Ch R = 1,166668,2210,2210,2210
BEGIN DESCRIPTION:
Mapping XS 53b68bd7
END DESCRIPTION:
XS GIS Cut Line= 3
      1675017.49      7046954.81      1674659.40      7045826.29
      1674876.41      7044513.37
#Sta/Elev= 30
  4195.9 1513.79  4450.8 1516.89  4612.2 1512.31  4655.0 1503.72  4664.7 1499.60
  4682.0 1484.74  4718.9 1468.45  4746.4 1460.57  4801.0 1439.20  4853.8 1406.02
  4874.5 1397.63  4918.3 1367.49  4953.8 1349.27  4977.6 1340.72  4982.5 1334.65
  4986.2 1333.65  5027.5 1334.65  5030.9 1334.66  5042.2 1337.53  5063.3 1350.52
  5094.8 1349.25  5112.0 1341.83  5239.3 1349.76  5283.8 1362.59  5342.9 1369.63
  5763.3 1374.35  6365.5 1365.57  6523.5 1370.82  6594.4 1381.35  6710.6 1386.83
#Mann=9,-1,0
  4195.9    0.05       0  4718.9    0.12       0  4746.4    0.05       0
  4953.8    0.12       0  4982.5    0.07       0  5027.5    0.12       0
  5030.9    0.05       0  5239.3    0.12       0  5342.9    0.05       0
Bank Sta=4982.5,5027.5
Exp/Cntr=0.3,0.1

Type RM Length L Ch R = 1,164458,2293,2293,2293
BEGIN DESCRIPTION:
Mapping XS ce9c240d
END DESCRIPTION:
XS GIS Cut Line= 2
      1676438.89      7044784.61      1674843.89      7043808.08
#Sta/Elev= 30
  4327.5 1511.37  4450.3 1515.99  4496.2 1514.88  4560.6 1500.87  4566.6 1496.69
  4597.3 1487.17  4612.7 1485.55  4655.3 1468.61  4719.2 1461.27  4756.8 1449.28
  4771.4 1442.75  4786.9 1431.35  4829.5 1410.21  4844.9 1398.86  4924.2 1351.08
  4945.5 1347.01  4974.9 1331.12  4977.9 1330.12  5010.9 1331.12  5012.1 1334.31
  5061.6 1337.33  5082.9 1346.92  5150.5 1357.29  5177.7 1366.39  5287.9 1378.76
  5334.2 1376.83  5446.6 1377.70  5514.2 1392.18  5593.6 1397.35  6197.7 1409.06
#Mann=5,-1,0
  4327.5    0.05       0  4756.8    0.12       0  4974.9    0.07       0
  5010.9    0.12       0  5334.2    0.05       0
Bank Sta=4974.9,5010.9
Exp/Cntr=0.3,0.1

Type RM Length L Ch R = 1,162165,1060,1060,1060
BEGIN DESCRIPTION:
Clear Fork Brazos Rv 42.0
END DESCRIPTION:
XS GIS Cut Line= 3
      1676204.95      7042338.00      1675705.00      7042338.00
      1675204.95      7042338.00
#Sta/Elev= 30
  4514.0 1429.55  4516.5 1429.55  4524.0 1423.51  4544.0 1411.38  4554.0 1401.45
  4564.0 1396.98  4571.9 1395.87  4584.0 1392.58  4624.0 1368.44  4644.0 1358.46
  4654.0 1356.08  4664.0 1351.80  4764.0 1343.29  4804.0 1338.12  4934.0 1335.13
  4966.4 1329.87  4970.9 1328.87  5020.4 1329.87  5024.0 1337.13  5034.0 1347.99
  5044.0 1355.47  5054.0 1359.85  5064.0 1361.27  5074.0 1369.40  5164.0 1370.58
  5204.0 1377.03  5224.0 1381.68  5254.0 1385.23  5334.0 1387.08  5514.0 1399.77
#Mann=4,-1,0
  4514.0    0.05       0  4571.9    0.12       0  4966.4    0.05       0
  5020.4    0.05       0
Bank Sta=4966.4,5020.4
Exp/Cntr=0.3,0.1

Type RM Length L Ch R = 1,161105,1445,1445,1445
BEGIN DESCRIPTION:
Mapping XS 990d2614
END DESCRIPTION:
XS GIS Cut Line= 2
      1676406.33      7041171.35      1674409.90      7041746.41
#Sta/Elev= 30
  4336.2 1438.16  4560.1 1432.89  4681.0 1422.40  4734.9 1425.18  4777.8 1423.19
  4805.9 1415.27  4857.9 1384.08  4878.7 1377.56  4907.6 1359.49  4930.8 1346.76
  4956.6 1340.86  4967.1 1329.77  4971.6 1328.77  5021.1 1329.77  5053.0 1332.21
  5068.0 1343.78  5096.5 1347.96  5118.1 1338.14  5159.7 1348.96  5169.0 1348.16
  5174.2 1340.55  5225.8 1347.29  5246.8 1352.57  5263.8 1364.80  5391.9 1368.19
  5430.7 1378.23  5643.2 1376.49  5855.6 1388.17  5961.0 1383.78  6413.8 1397.37
#Mann=7,-1,0
  4336.2    0.05       0  4734.9    0.12       0  4907.6    0.05       0
  4967.1    0.05       0  5021.1    0.05       0  5053.0    0.12       0
  5225.8    0.05       0
Bank Sta=4967.1,5021.1
Exp/Cntr=0.3,0.1

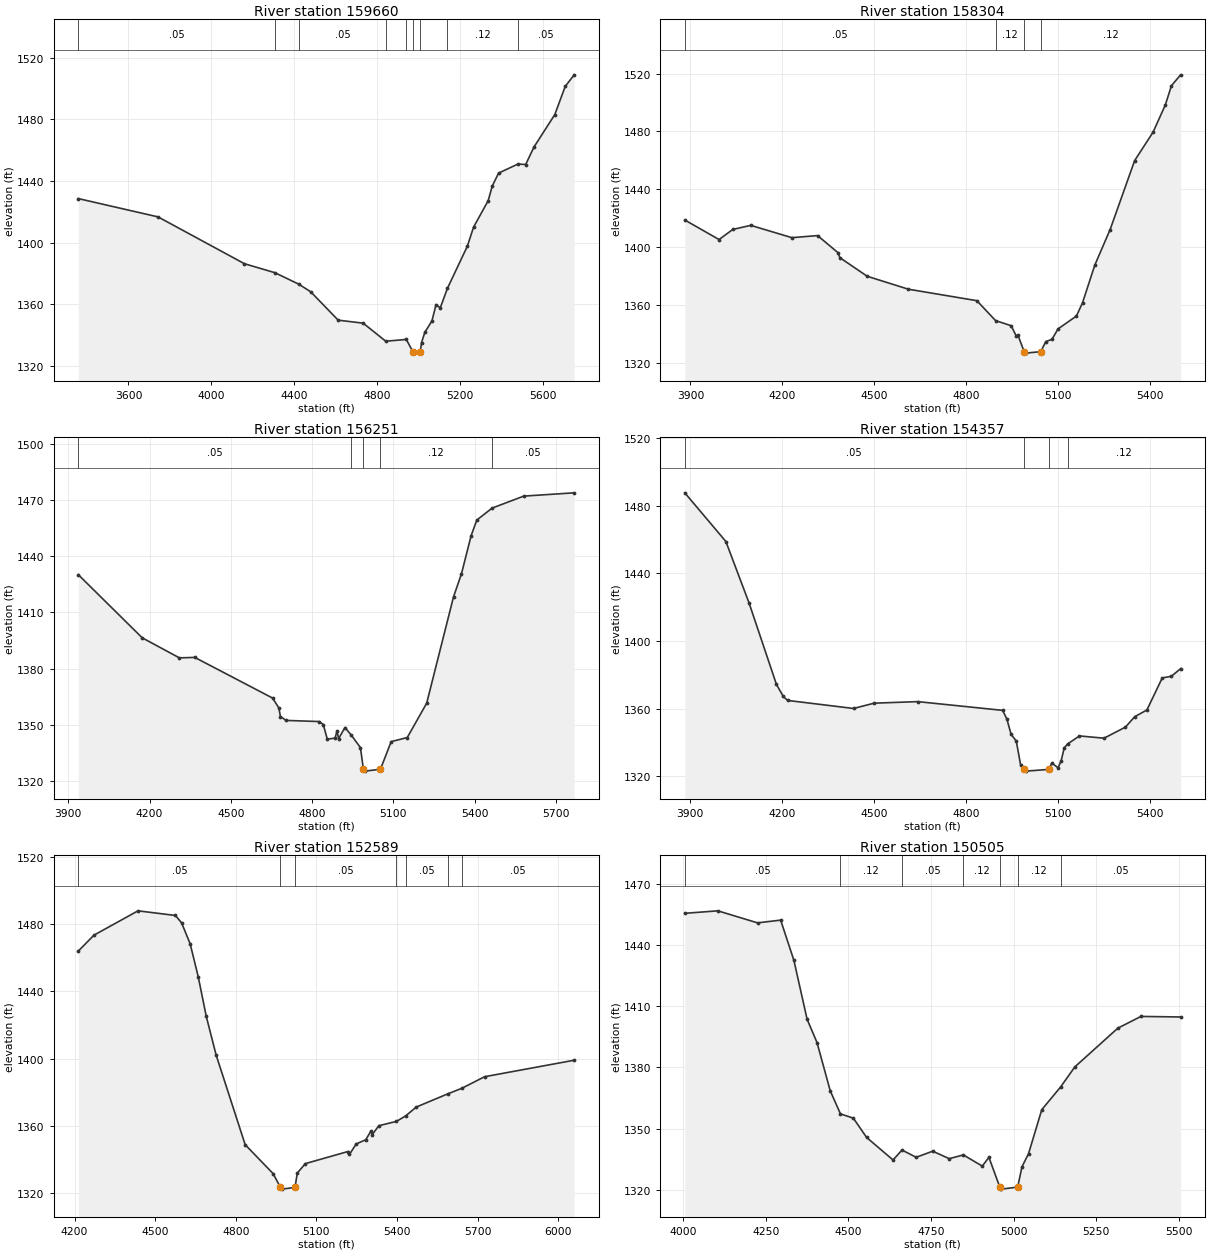
Type RM Length L Ch R = 1,159660,1356,1356,1356
BEGIN DESCRIPTION:
Mapping XS b53116f6
END DESCRIPTION:
XS GIS Cut Line= 3
      1676525.70      7040813.26      1675462.35      7040183.93
      1674312.18      7040075.42
#Sta/Elev= 30
  3358.1 1428.53  3742.4 1416.64  4159.2 1386.21  4306.1 1380.38  4422.2 1372.85
  4479.0 1367.94  4611.2 1349.54  4731.7 1347.59  4840.4 1335.88  4939.6 1337.01
  4971.1 1329.13  4974.1 1328.13  5007.1 1329.13  5012.9 1334.87  5028.8 1341.62
  5063.2 1349.06  5083.2 1359.69  5103.3 1357.51  5138.1 1370.28  5233.9 1397.57
  5264.0 1410.00  5334.4 1427.18  5354.4 1436.80  5384.6 1445.08  5478.1 1450.99
  5515.2 1450.66  5555.3 1462.04  5655.8 1483.15  5706.0 1501.43  5749.0 1508.94
#Mann=9,-1,0
  3358.1    0.05       0  4306.1    0.12       0  4422.2    0.05       0
  4840.4    0.12       0  4939.6    0.05       0  4971.1    0.05       0
  5007.1    0.05       0  5138.1    0.12       0  5478.1    0.05       0
Bank Sta=4971.1,5007.1
Exp/Cntr=0.3,0.1

Type RM Length L Ch R = 1,158304,2053,2053,2053
BEGIN DESCRIPTION:
Clear Fork Brazos Rv 41.0
END DESCRIPTION:
XS GIS Cut Line= 3
      1676705.01      7040688.03      1676205.00      7039688.00
      1676205.00      7039187.97
#Sta/Elev= 30
  3881.7 1418.65  3993.5 1405.13  4038.3 1412.12  4097.0 1414.94  4231.1 1406.43
  4315.0 1407.87  4382.1 1395.96  4387.6 1392.61  4477.1 1379.71  4611.2 1370.78
  4834.9 1362.83  4895.7 1349.08  4946.7 1345.51  4963.4 1338.39  4969.0 1338.94
  4989.2 1327.55  4993.7 1326.55  5043.2 1327.55  5059.8 1334.52  5079.8 1336.07
  5099.8 1343.31  5159.8 1352.21  5179.8 1361.47  5219.8 1387.48  5269.8 1412.08
  5349.8 1459.77  5409.8 1479.40  5449.8 1498.19  5469.8 1511.56  5499.8 1519.09
#Mann=4,-1,0
  3881.7    0.05       0  4895.7    0.12       0  4989.2    0.07       0
  5043.2    0.12       0
Bank Sta=4989.2,5043.2
Exp/Cntr=0.3,0.1

Type RM Length L Ch R = 1,156251,1894,1894,1894
BEGIN DESCRIPTION:
Mapping XS 85cbe062
END DESCRIPTION:
XS GIS Cut Line= 2
      1677024.85      7041236.45      1678531.54      7040195.86
#Sta/Elev= 30
  3936.9 1430.12  4172.9 1396.49  4310.1 1385.82  4366.9 1386.06  4654.1 1364.42
  4677.2 1359.21  4683.3 1354.58  4704.2 1352.50  4826.6 1351.89  4841.5 1350.31
  4856.3 1342.52  4885.0 1343.07  4892.2 1346.84  4898.2 1342.83  4921.5 1348.72
  4944.6 1344.73  4978.7 1338.01  4989.7 1326.48  4995.0 1325.48  5052.7 1326.48
  5092.2 1341.20  5151.7 1343.38  5223.4 1361.69  5322.5 1418.32  5351.8 1430.59
  5387.6 1450.97  5408.6 1459.24  5464.8 1465.59  5581.7 1471.99  5768.0 1473.74
#Mann=5,-1,0
  3936.9    0.05       0  4944.6    0.12       0  4989.7    0.07       0
  5052.7    0.12       0  5464.8    0.05       0
Bank Sta=4989.7,5052.7
Exp/Cntr=0.3,0.1

Type RM Length L Ch R = 1,154357,1768,1768,1768
BEGIN DESCRIPTION:
Clear Fork Brazos Rv 40.0
END DESCRIPTION:
XS GIS Cut Line= 3
      1678605.01      7042987.98      1679105.00      7041988.00
      1679105.00      7041488.01
#Sta/Elev= 30
  3882.3 1487.64  4016.4 1458.85  4091.9 1422.56  4181.4 1374.34  4203.7 1367.24
  4217.7 1364.89  4432.9 1360.12  4500.0 1363.26  4642.5 1364.18  4919.3 1359.01
  4933.2 1353.96  4947.2 1344.76  4964.0 1340.87  4978.0 1326.89  4988.2 1324.08
  4995.0 1323.08  5069.2 1324.08  5080.3 1327.79  5100.3 1325.08  5110.3 1329.08
  5120.3 1336.76  5131.3 1339.14  5170.3 1343.89  5250.3 1342.55  5320.3 1349.11
  5350.3 1355.23  5390.3 1359.24  5440.3 1378.18  5470.3 1379.19  5500.3 1383.67
#Mann=4,-1,0
  3882.3    0.05       0  4988.2    0.03       0  5069.2    0.05       0
  5131.3    0.12       0
Bank Sta=4988.2,5069.2
Exp/Cntr=0.3,0.1

Type RM Length L Ch R = 1,152589,2084,2084,2084
BEGIN DESCRIPTION:
Mapping XS ff93f377
END DESCRIPTION:
XS GIS Cut Line= 2
      1680800.90      7043157.03      1680139.75      7041433.70
#Sta/Elev= 30
  4214.0 1463.91  4272.1 1473.33  4436.2 1487.80  4575.6 1485.04  4598.5 1480.63
  4630.3 1468.20  4660.3 1448.67  4690.3 1425.04  4727.1 1402.03  4835.1 1348.82
  4939.2 1331.62  4966.5 1323.41  4971.0 1322.41  5020.5 1323.41  5029.2 1331.98
  5059.3 1337.58  5218.0 1344.77  5223.3 1343.00  5248.0 1349.22  5284.0 1351.76
  5302.7 1356.75  5308.1 1354.83  5332.7 1360.10  5398.4 1362.67  5432.5 1365.92
  5472.1 1371.19  5589.3 1379.03  5642.1 1382.37  5726.3 1389.21  6059.8 1399.01
#Mann=7,-1,0
  4214.0    0.05       0  4966.5    0.05       0  5020.5    0.05       0
  5398.4    0.12       0  5432.5    0.05       0  5589.3    0.12       0
  5642.1    0.05       0
Bank Sta=4966.5,5020.5
Exp/Cntr=0.3,0.1

Type RM Length L Ch R = 1,150505,2391,2391,2391
BEGIN DESCRIPTION:
Clear Fork Brazos Rv 39.0
END DESCRIPTION:
XS GIS Cut Line= 3
      1681904.95      7040588.00      1680905.00      7040588.00
      1680404.95      7040588.00
#Sta/Elev= 30
  4004.9 1455.60  4104.9 1456.82  4224.9 1450.92  4294.9 1452.26  4334.9 1432.56
  4374.9 1403.65  4404.9 1392.22  4444.9 1368.56  4475.8 1357.26  4514.9 1355.14
  4554.9 1345.70  4634.9 1334.64  4661.9 1339.52  4704.9 1335.96  4754.9 1338.95
  4804.9 1335.29  4847.6 1337.12  4904.9 1331.64  4924.9 1335.94  4957.9 1321.35
  4962.4 1320.35  5011.9 1321.35  5024.9 1331.26  5044.9 1337.79  5084.9 1359.33
  5141.7 1370.42  5184.9 1380.29  5314.9 1399.28  5384.9 1405.04  5504.9 1404.77
#Mann=7,-1,0
  4004.9    0.05       0  4475.8    0.12       0  4661.9    0.05       0
  4847.6    0.12       0  4957.9    0.07       0  5011.9    0.12       0
  5141.7    0.05       0
Bank Sta=4957.9,5011.9
Exp/Cntr=0.3,0.1

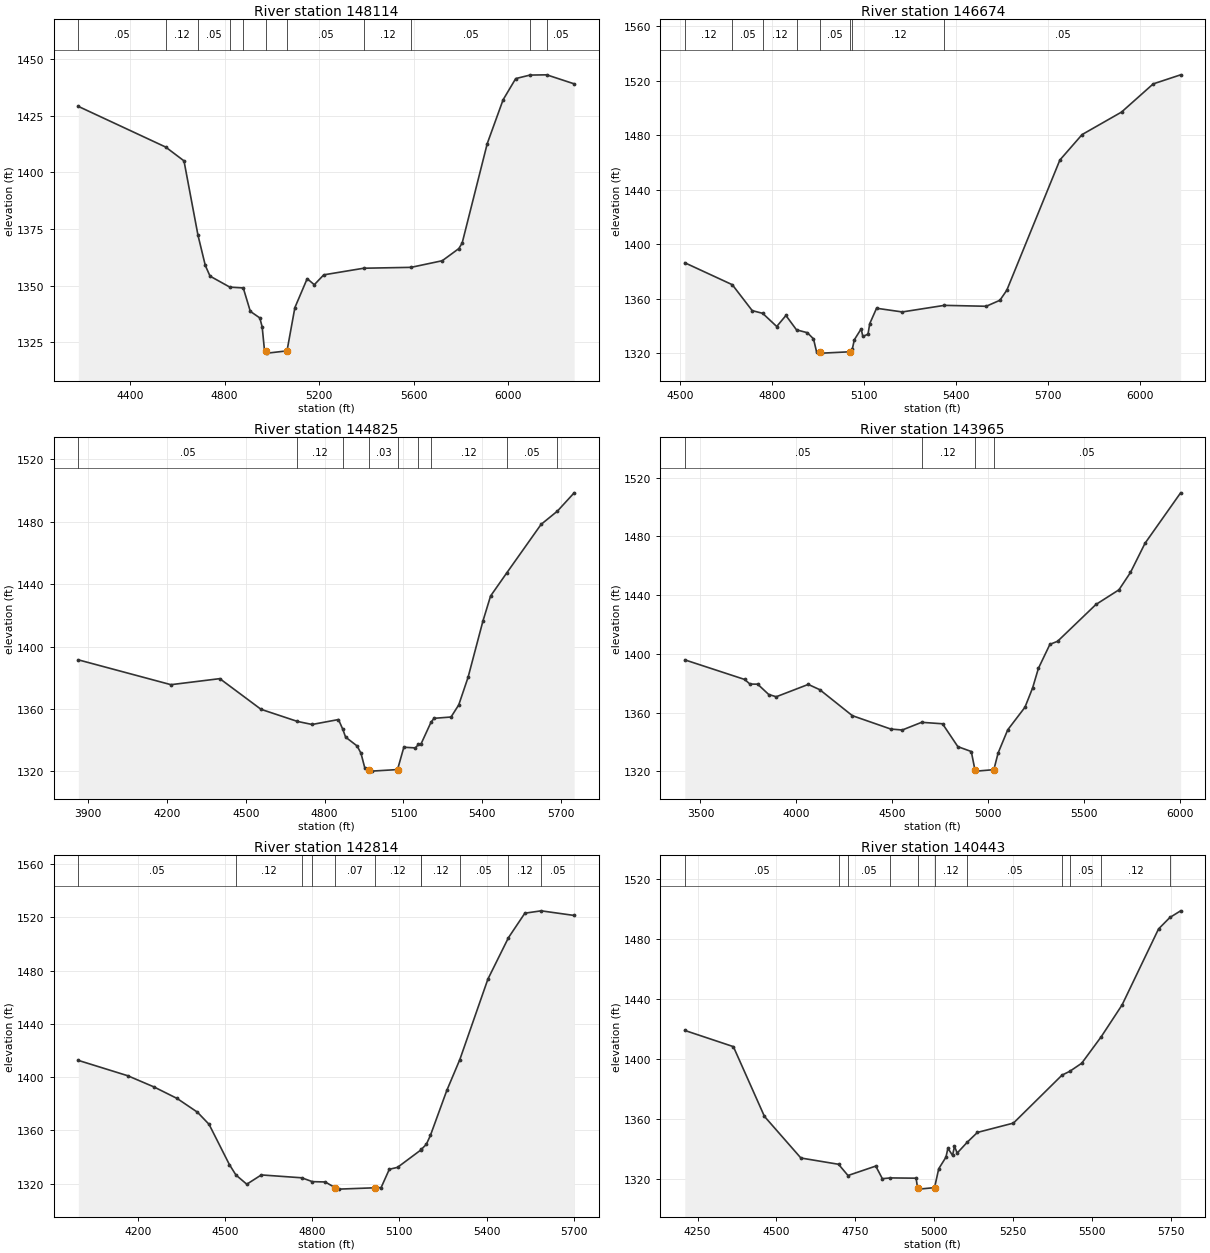
Type RM Length L Ch R = 1,148114,1440,1440,1440
BEGIN DESCRIPTION:
Mapping XS aa6fa04a
END DESCRIPTION:
XS GIS Cut Line= 2
      1681820.83      7038415.27      1679728.33      7038296.00
#Sta/Elev= 30
  4181.9 1429.17  4551.0 1411.22  4628.5 1405.12  4687.9 1372.17  4718.6 1358.96
  4738.6 1354.23  4822.5 1349.37  4879.1 1349.02  4908.9 1338.68  4949.0 1335.78
  4959.0 1331.83  4969.0 1321.24  4974.0 1321.24  4981.5 1320.24  5064.0 1321.24
  5097.3 1340.35  5149.3 1353.11  5179.3 1350.44  5219.4 1354.80  5388.1 1357.72
  5588.5 1358.11  5720.2 1361.03  5790.3 1366.39  5804.4 1368.85  5910.5 1412.77
  5977.4 1432.08  6030.7 1441.44  6091.1 1442.99  6161.8 1443.10  6277.8 1439.12
#Mann=11,-1,0
  4181.9    0.05       0  4551.0    0.12       0  4687.9    0.05       0
  4822.5    0.12       0  4879.1    0.05       0  4974.0    0.05       0
  5064.0    0.05       0  5388.1    0.12       0  5588.5    0.05       0
  6091.1    0.12       0  6161.8    0.05       0
Bank Sta=4974,5064
Exp/Cntr=0.3,0.1

Type RM Length L Ch R = 1,146674,1849,1849,1849
BEGIN DESCRIPTION:
Clear Fork Brazos Rv 38.0
END DESCRIPTION:
XS GIS Cut Line= 3
      1681105.04      7037038.00      1680605.00      7037038.00
      1679604.98      7036537.99
#Sta/Elev= 30
  4515.0 1386.50  4670.0 1370.41  4735.0 1351.40  4769.1 1349.41  4815.0 1339.75
  4845.0 1347.83  4879.6 1337.29  4915.0 1335.20  4935.0 1330.68  4945.0 1321.22
  4956.0 1321.22  4964.3 1320.22  5055.0 1321.22  5061.9 1323.42  5068.2 1330.00
  5090.5 1338.01  5096.1 1332.43  5112.9 1334.13  5118.5 1341.82  5140.8 1353.14
  5224.7 1350.43  5362.1 1355.26  5498.6 1354.59  5543.3 1358.99  5565.7 1366.31
  5739.0 1461.86  5811.6 1480.55  5940.2 1497.03  6043.6 1517.71  6133.1 1524.36
#Mann=8,-1,0
  4515.0    0.12       0  4670.0    0.05       0  4769.1    0.12       0
  4879.6    0.05       0  4956.0    0.05       0  5055.0    0.05       0
  5061.9    0.12       0  5362.1    0.05       0
Bank Sta=4956,5055
Exp/Cntr=0.3,0.1

Type RM Length L Ch R = 1,144825,860,860,860
BEGIN DESCRIPTION:
Mapping XS 2071092e
END DESCRIPTION:
XS GIS Cut Line= 2
      1681679.78      7036375.30      1680562.17      7034856.23
#Sta/Elev= 30
  3863.4 1391.51  4215.6 1375.59  4401.5 1379.46  4558.2 1359.80  4696.1 1352.06
  4752.5 1350.07  4852.8 1353.23  4869.4 1346.96  4879.9 1341.98  4923.8 1336.28
  4938.5 1331.62  4952.6 1322.45  4969.5 1321.16  4978.5 1320.16  5077.5 1321.16
  5101.5 1335.48  5145.2 1335.06  5157.2 1337.28  5166.1 1337.31  5204.8 1351.50
  5216.2 1354.02  5281.0 1354.86  5310.3 1362.62  5345.8 1380.32  5402.1 1416.25
  5431.4 1432.44  5492.0 1447.04  5623.6 1478.38  5685.5 1486.86  5749.3 1498.60
#Mann=9,-1,0
  3863.4    0.05       0  4696.1    0.12       0  4869.4    0.05       0
  4969.5    0.03       0  5077.5    0.05       0  5157.2    0.05       0
  5204.8    0.12       0  5492.0    0.05       0  5685.5    0.12       0
Bank Sta=4969.5,5077.5
Exp/Cntr=0.3,0.1

Type RM Length L Ch R = 1,143965,1151,1151,1151
BEGIN DESCRIPTION:
Mapping XS 08306185
END DESCRIPTION:
XS GIS Cut Line= 3
      1681812.06      7036374.98      1681599.26      7035918.98
      1681523.26      7033836.38
#Sta/Elev= 30
  3418.1 1395.90  3729.8 1382.57  3758.2 1379.41  3798.4 1379.32  3856.2 1372.27
  3895.4 1370.76  4062.4 1379.16  4122.4 1375.57  4292.5 1357.85  4492.7 1348.75
  4552.7 1348.09  4654.0 1353.33  4762.9 1352.33  4842.9 1336.74  4913.0 1333.43
  4931.8 1321.06  4940.1 1320.06  5030.8 1321.06  5053.0 1332.42  5103.1 1348.20
  5193.1 1363.62  5233.2 1376.85  5263.2 1390.10  5323.2 1406.47  5363.3 1408.55
  5563.4 1433.64  5683.5 1443.64  5743.5 1455.44  5819.5 1475.36  6005.3 1509.74
#Mann=4,-1,0
  3418.1    0.05       0  4654.0    0.12       0  4931.8    0.05       0
  5030.8    0.05       0
Bank Sta=4931.8,5030.8
Exp/Cntr=0.3,0.1

Type RM Length L Ch R = 1,142814,2371,2371,2371
BEGIN DESCRIPTION:
Clear Fork Brazos Rv 37.0
END DESCRIPTION:
XS GIS Cut Line= 3
      1682455.00      7036437.98      1682455.00      7035438.00
      1682955.01      7034937.99
#Sta/Elev= 30
  3994.7 1412.56  4164.7 1401.05  4254.7 1392.68  4334.7 1383.99  4404.7 1373.68
  4444.7 1364.59  4514.7 1334.39  4537.4 1326.50  4574.7 1319.61  4624.7 1326.58
  4764.0 1324.42  4800.4 1321.54  4844.7 1321.30  4879.6 1316.92  4890.8 1315.92
  5014.6 1316.92  5037.1 1317.04  5065.4 1330.82  5093.7 1332.27  5173.4 1345.21
  5175.6 1345.76  5192.7 1349.50  5206.8 1356.19  5263.4 1390.04  5308.2 1413.19
  5404.8 1473.56  5475.5 1504.64  5532.1 1523.06  5588.2 1524.83  5701.8 1521.36
#Mann=11,-1,0
  3994.7    0.05       0  4537.4    0.12       0  4764.0    0.05       0
  4800.4    0.12       0  4879.6    0.07       0  5014.6    0.12       0
  5173.4    0.05       0  5175.6    0.12       0  5308.2    0.05       0
  5475.5    0.12       0  5588.2    0.05       0
Bank Sta=4879.6,5014.6
Exp/Cntr=0.3,0.1

Type RM Length L Ch R = 1,140443,1423,1423,1423
BEGIN DESCRIPTION:
Mapping XS 55faf83e
END DESCRIPTION:
XS GIS Cut Line= 2
      1683459.30      7037145.74      1684739.71      7036234.27
#Sta/Elev= 30
  4209.7 1419.22  4363.7 1408.42  4462.2 1361.92  4577.7 1334.21  4697.0 1330.03
  4727.0 1322.54  4815.0 1328.83  4835.9 1320.44  4861.7 1320.94  4942.9 1320.76
  4947.4 1314.47  4951.9 1313.47  5001.4 1314.47  5014.6 1327.05  5037.5 1334.76
  5043.7 1340.69  5058.4 1335.96  5064.6 1341.95  5073.2 1337.50  5105.4 1344.82
  5137.3 1351.26  5251.5 1357.48  5405.5 1389.45  5430.1 1391.99  5467.9 1397.37
  5529.5 1414.96  5595.8 1436.20  5711.4 1486.85  5747.3 1494.48  5781.4 1498.92
#Mann=11,-1,0
  4209.7    0.05       0  4697.0    0.12       0  4727.0    0.05       0
  4861.7    0.12       0  4947.4    0.07       0  5001.4    0.12       0
  5105.4    0.05       0  5405.5    0.12       0  5430.1    0.05       0
  5529.5    0.12       0  5747.3    0.05       0
Bank Sta=4947.4,5001.4
Exp/Cntr=0.3,0.1

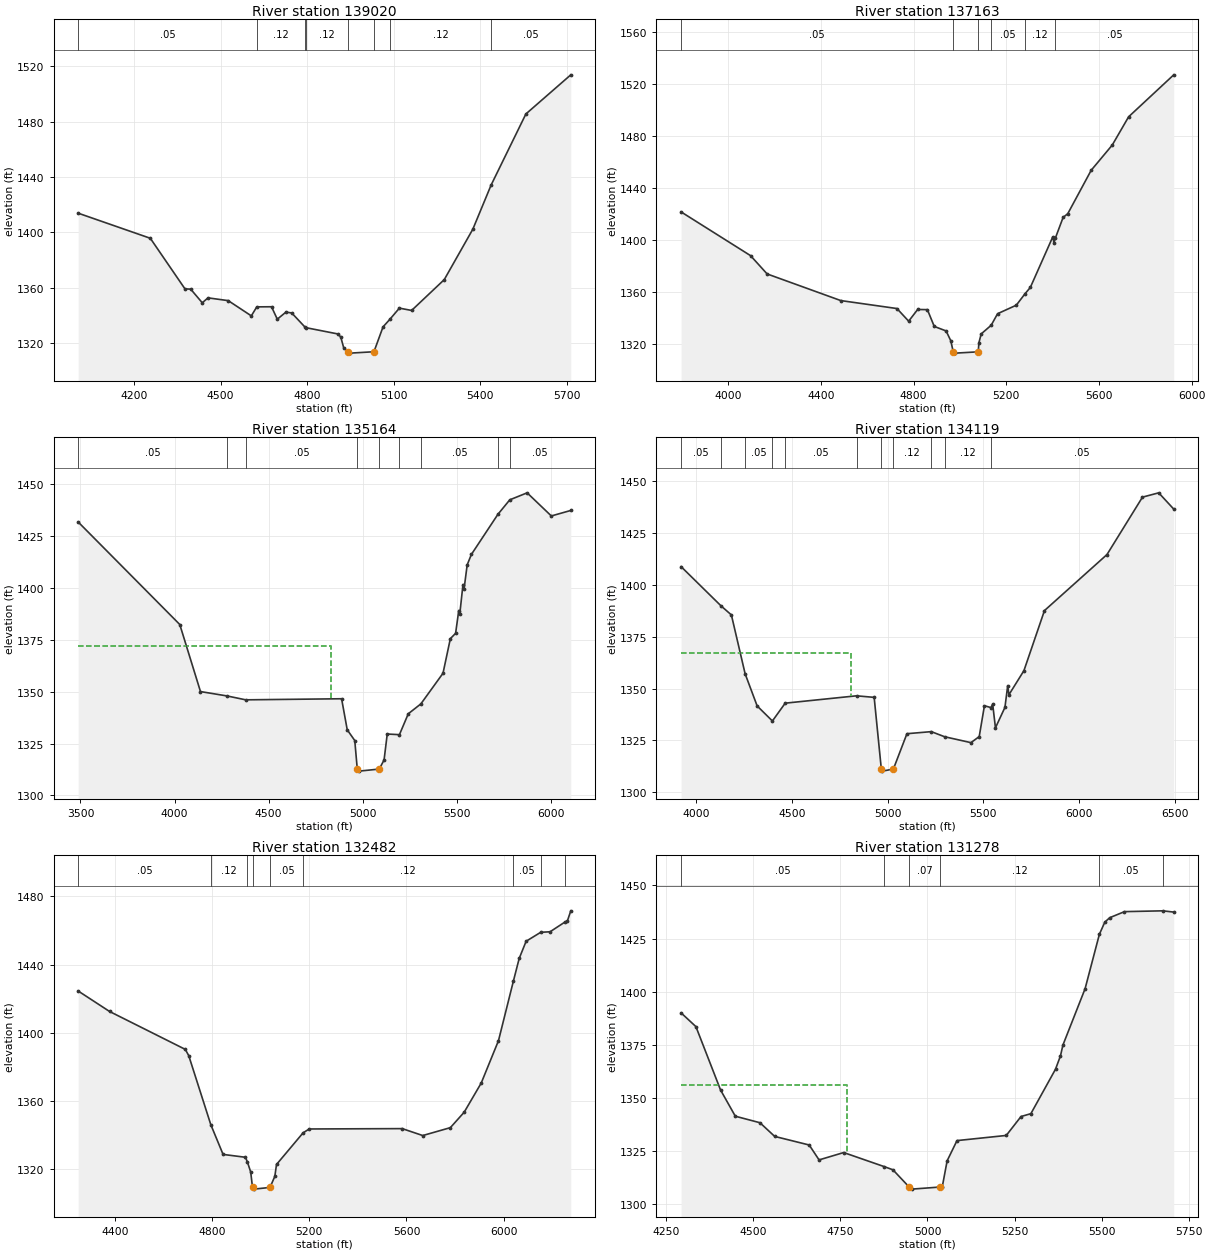
Type RM Length L Ch R = 1,139020,1857,1857,1857
BEGIN DESCRIPTION:
Clear Fork Brazos Rv 36.0
END DESCRIPTION:
XS GIS Cut Line= 3
      1683855.05      7037838.00      1684855.00      7037838.00
      1685355.03      7037337.97
#Sta/Elev= 30
  4006.7 1413.94  4256.7 1395.79  4376.7 1359.24  4396.7 1359.01  4436.7 1349.17
  4456.7 1352.72  4526.7 1350.72  4606.7 1339.71  4625.7 1346.21  4676.7 1346.29
  4696.7 1337.31  4726.7 1342.42  4746.7 1341.81  4793.5 1331.42  4795.3 1331.20
  4906.7 1326.63  4916.7 1324.39  4926.7 1316.74  4941.7 1313.77  4949.2 1312.77
  5031.7 1313.77  5063.2 1331.77  5086.6 1337.16  5119.8 1345.30  5162.2 1343.62
  5275.4 1365.93  5374.4 1402.39  5437.8 1434.33  5558.2 1485.66  5713.8 1513.95
#Mann=8,-1,0
  4006.7    0.05       0  4625.7    0.12       0  4793.5    0.05       0
  4795.3    0.12       0  4941.7    0.03       0  5031.7    0.12       0
  5086.6    0.12       0  5437.8    0.05       0
Bank Sta=4941.7,5031.7
Exp/Cntr=0.3,0.1

Type RM Length L Ch R = 1,137163,1999,1999,1999
BEGIN DESCRIPTION:
Mapping XS 6ff884f1
END DESCRIPTION:
XS GIS Cut Line= 2
      1684012.66      7039391.82      1686117.77      7039684.80
#Sta/Elev= 30
  3797.3 1421.46  4096.8 1387.78  4168.4 1373.67  4486.2 1353.15  4728.5 1347.02
  4779.0 1337.28  4817.9 1346.29  4859.8 1346.17  4889.5 1333.23  4940.6 1329.75
  4960.7 1322.24  4971.4 1313.66  4980.4 1312.66  5079.4 1313.66  5081.9 1320.50
  5092.0 1327.46  5135.0 1334.12  5162.7 1343.03  5243.4 1349.59  5281.3 1358.46
  5304.0 1363.28  5400.9 1402.29  5405.9 1397.79  5411.6 1401.12  5445.4 1417.22
  5465.6 1420.12  5566.5 1453.54  5657.4 1472.97  5728.1 1494.76  5922.7 1527.09
#Mann=6,-1,0
  3797.3    0.05       0  4971.4    0.03       0  5079.4    0.05       0
  5135.0    0.05       0  5281.3    0.12       0  5411.6    0.05       0
Bank Sta=4971.4,5079.4
Exp/Cntr=0.3,0.1

Type RM Length L Ch R = 1,135164,1045,1045,1045
BEGIN DESCRIPTION:
Clear Fork Brazos Rv 35.0
END DESCRIPTION:
XS GIS Cut Line= 3
      1683404.97      7041438.00      1684905.00      7041438.00
      1685905.03      7040937.98
#Sta/Elev= 30
  3487.7 1431.72  4027.7 1382.34  4137.7 1350.04  4279.1 1347.93  4378.1 1346.06
  4887.7 1346.58  4917.7 1331.62  4957.7 1326.45  4971.0 1312.72  4980.8 1311.72
  5088.0 1312.72  5113.5 1317.13  5130.3 1329.59  5195.1 1329.28  5242.1 1339.35
  5308.9 1344.10  5426.6 1358.86  5465.7 1375.53  5493.6 1378.10  5510.4 1389.09
  5516.0 1387.54  5532.8 1401.59  5538.4 1399.33  5555.1 1411.06  5577.5 1416.10
  5718.3 1435.40  5781.5 1442.40  5873.8 1445.77  6002.3 1434.63  6105.8 1437.28
#Mann=9,-1,0
  3487.7    0.05       0  4279.1    0.12       0  4378.1    0.05       0
  4971.0    0.05       0  5088.0    0.05       0  5195.1    0.12       0
  5308.9    0.05       0  5718.3    0.12       0  5781.5    0.05       0
#XS Ineff=2,0
    0.00 4833.10 1372.22               0
Permanent Ineff=
       F       F
Bank Sta=4971,5088
Exp/Cntr=0.3,0.1

Type RM Length L Ch R = 1,134119,1637,1637,1637
BEGIN DESCRIPTION:
Mapping XS 0f11ae0f
END DESCRIPTION:
XS GIS Cut Line= 2
      1683560.26      7041604.32      1685566.86      7043215.68
#Sta/Elev= 30
  3921.5 1408.87  4130.1 1389.93  4184.1 1385.57  4255.9 1357.16  4318.7 1341.64
  4398.4 1334.38  4465.2 1342.98  4838.0 1346.53  4930.0 1345.78  4967.4 1311.18
  4972.6 1310.18  5030.4 1311.18  5101.2 1328.24  5228.5 1329.24  5297.9 1326.78
  5435.6 1323.93  5478.8 1326.85  5506.0 1341.74  5539.7 1340.86  5549.2 1342.46
  5563.6 1331.09  5613.2 1340.95  5627.6 1351.45  5634.0 1347.05  5712.4 1358.68
  5819.6 1387.66  6146.3 1414.71  6331.7 1442.42  6416.5 1444.50  6495.0 1436.65
#Mann=11,-1,0
  3921.5    0.05       0  4130.1    0.12       0  4255.9    0.05       0
  4398.4    0.12       0  4465.2    0.05       0  4838.0    0.12       0
  4967.4    0.07       0  5030.4    0.12       0  5228.5    0.05       0
  5297.9    0.12       0  5539.7    0.05       0
#XS Ineff=2,0
    0.00 4811.20 1367.07               0
Permanent Ineff=
       F       F
Bank Sta=4967.4,5030.4
Exp/Cntr=0.3,0.1

Type RM Length L Ch R = 1,132482,1204,1204,1204
BEGIN DESCRIPTION:
Mapping XS 54ff5e82
END DESCRIPTION:
XS GIS Cut Line= 2
      1682743.19      7042397.49      1684250.24      7043752.75
#Sta/Elev= 30
  4249.4 1424.52  4378.4 1412.52  4690.1 1390.26  4704.3 1386.59  4795.2 1346.03
  4845.6 1328.62  4937.7 1326.94  4946.0 1324.04  4959.2 1318.32  4966.7 1309.25
  4972.7 1308.25  5038.7 1309.25  5058.6 1315.78  5065.4 1322.71  5174.8 1341.29
  5199.9 1343.55  5582.6 1343.76  5667.1 1339.70  5780.7 1344.33  5837.5 1353.38
  5907.7 1370.51  5978.7 1395.38  6040.3 1430.49  6064.0 1443.67  6092.4 1453.72
  6152.5 1458.97  6191.0 1459.28  6251.3 1464.91  6262.0 1465.57  6276.2 1471.57
#Mann=9,-1,0
  4249.4    0.05       0  4795.2    0.12       0  4946.0    0.05       0
  4966.7    0.03       0  5038.7    0.05       0  5174.8    0.12       0
  6040.3    0.05       0  6152.5    0.12       0  6251.3    0.05       0
Bank Sta=4966.7,5038.7
Exp/Cntr=0.3,0.1

Type RM Length L Ch R = 1,131278,1665,1665,1665
BEGIN DESCRIPTION:
Clear Fork Brazos Rv 34.0
END DESCRIPTION:
XS GIS Cut Line= 3
      1682454.97      7043437.97      1682955.00      7043938.00
      1683454.97      7044437.97
#Sta/Elev= 30
  4292.7 1390.05  4335.2 1383.59  4405.9 1353.81  4448.3 1341.47  4519.0 1338.41
  4561.4 1331.97  4660.4 1327.94  4688.7 1320.93  4759.4 1324.39  4875.3 1317.80
  4900.8 1316.28  4947.3 1308.19  4954.8 1307.19  5037.3 1308.19  5042.3 1308.19
  5056.4 1320.52  5084.7 1330.01  5226.1 1332.43  5268.5 1341.33  5296.8 1342.67
  5367.5 1363.58  5381.7 1369.82  5388.8 1374.94  5452.4 1401.42  5493.5 1427.04
  5509.0 1432.71  5523.1 1434.81  5565.5 1437.66  5675.4 1438.04  5706.9 1437.45
#Mann=6,-1,0
  4292.7    0.05       0  4875.3    0.12       0  4947.3    0.07       0
  5037.3    0.12       0  5493.5    0.05       0  5675.4    0.12       0
#XS Ineff=2,0
    0.00 4768.20 1355.98               0
Permanent Ineff=
       F       F
Bank Sta=4947.3,5037.3
Exp/Cntr=0.3,0.1