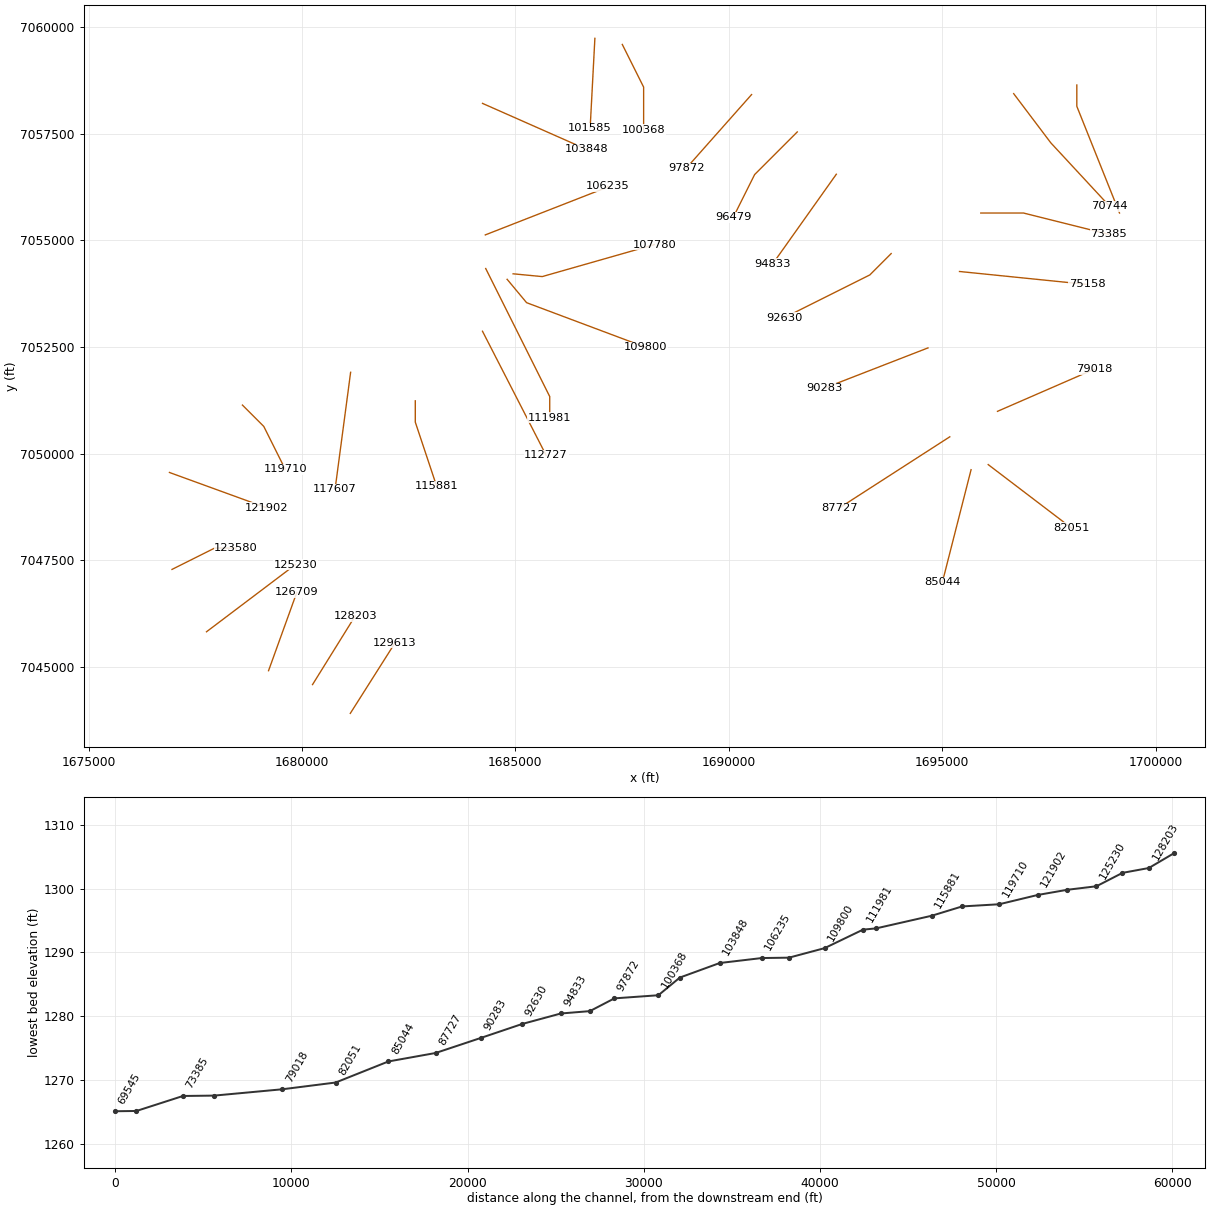
HEC-RAS study Clear Fork Brazos Rv.prj: Clear Fork Brazos Rv Base Level Engineering

--- Clear Fork Brazos Rv.g01 (geometry) --- (continued)

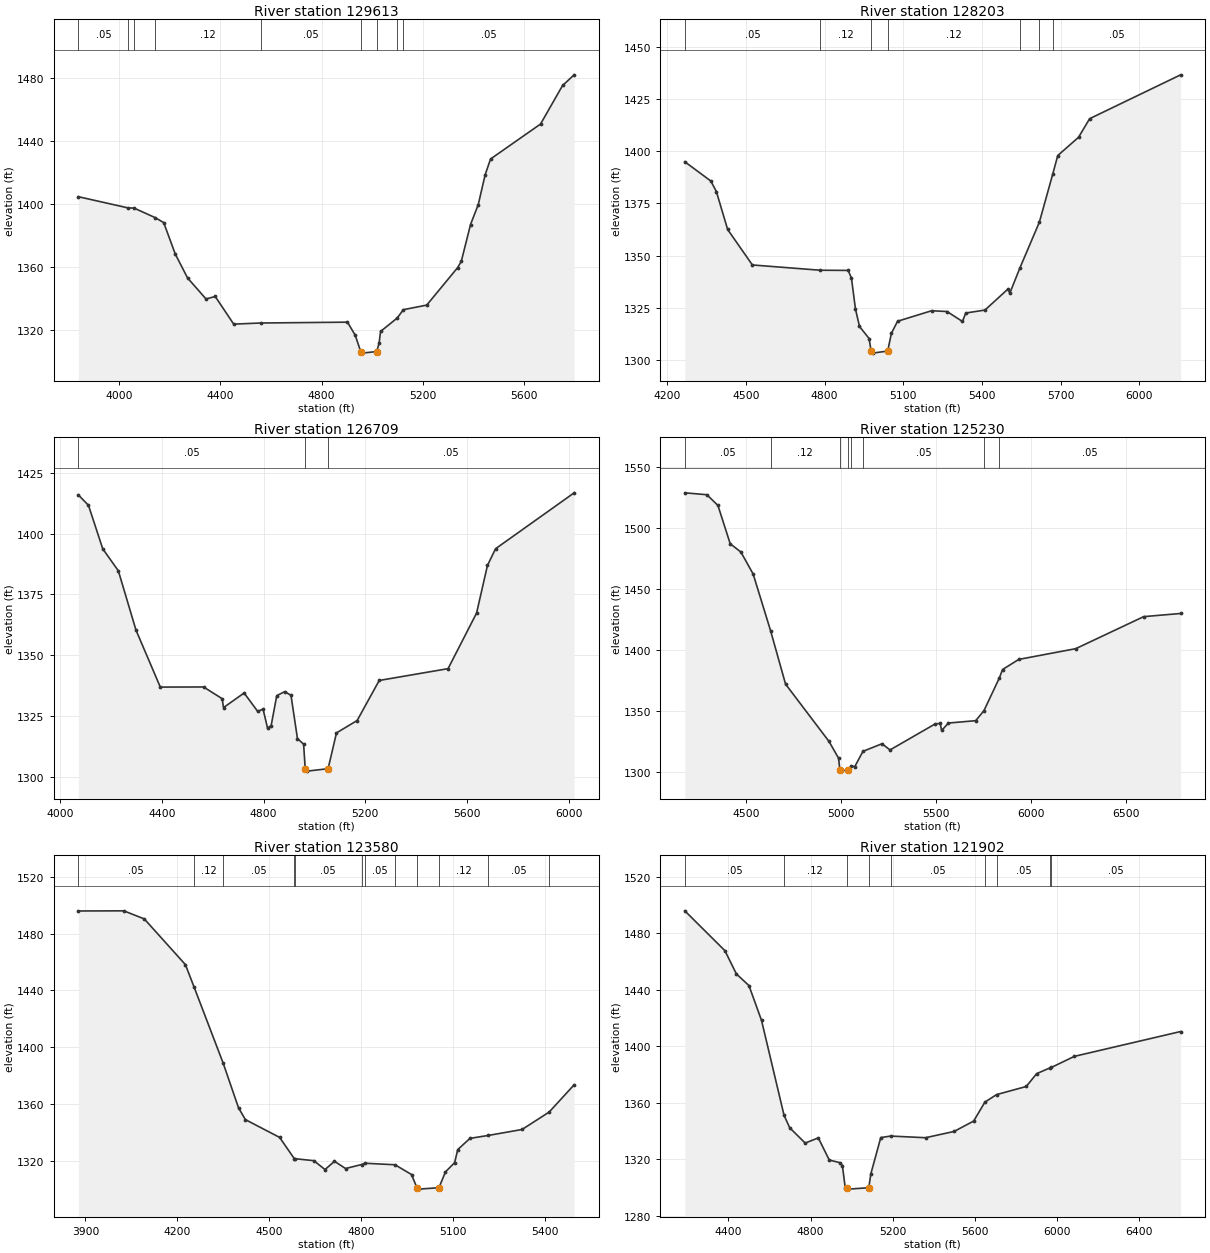
Type RM Length L Ch R = 1,129613,1410,1410,1410
BEGIN DESCRIPTION:
Mapping XS 46c92700
END DESCRIPTION:
XS GIS Cut Line= 2
      1681132.18      7043914.40      1682180.18      7045566.54
#Sta/Elev= 30
  3840.3 1404.64  4037.5 1397.50  4059.7 1397.46  4144.7 1391.29  4177.2 1388.21
  4222.9 1368.29  4271.2 1353.19  4344.1 1339.85  4380.5 1341.41  4453.4 1323.90
  4560.6 1324.61  4902.4 1325.14  4932.9 1316.84  4954.5 1306.52  4959.8 1305.52
  5017.5 1306.52  5027.0 1311.70  5032.9 1319.25  5098.3 1327.73  5122.9 1333.05
  5215.0 1335.95  5336.7 1359.63  5351.4 1363.65  5387.9 1387.01  5418.4 1399.64
  5445.5 1418.50  5466.9 1428.53  5664.1 1450.67  5751.2 1475.12  5796.8 1481.86
#Mann=9,-1,0
  3840.3    0.05       0  4037.5    0.12       0  4059.7    0.05       0
  4144.7    0.12       0  4560.6    0.05       0  4954.5    0.03       0
  5017.5    0.05       0  5098.3    0.12       0  5122.9    0.05       0
Bank Sta=4954.5,5017.5
Exp/Cntr=0.3,0.1

Type RM Length L Ch R = 1,128203,1494,1494,1494
BEGIN DESCRIPTION:
Mapping XS 6a87f5b6
END DESCRIPTION:
XS GIS Cut Line= 2
      1680247.49      7044589.28      1681245.07      7046194.09
#Sta/Elev= 30
  4267.4 1395.00  4366.4 1385.78  4387.7 1380.71  4430.7 1362.52  4524.9 1345.51
  4783.2 1342.98  4889.9 1342.89  4902.4 1339.29  4917.8 1324.40  4933.1 1316.04
  4969.7 1310.23  4977.6 1304.23  4982.9 1303.23  5040.6 1304.23  5054.8 1312.77
  5078.3 1318.52  5207.9 1323.55  5266.7 1323.19  5325.6 1318.40  5338.1 1322.46
  5411.3 1323.88  5499.9 1334.07  5505.7 1331.86  5544.2 1344.00  5618.5 1365.97
  5670.0 1389.25  5688.8 1397.98  5767.9 1406.72  5810.3 1415.65  6157.0 1436.68
#Mann=7,-1,0
  4267.4    0.05       0  4783.2    0.12       0  4977.6    0.07       0
  5040.6    0.12       0  5544.2    0.05       0  5618.5    0.12       0
  5670.0    0.05       0
Bank Sta=4977.6,5040.6
Exp/Cntr=0.3,0.1

Type RM Length L Ch R = 1,126709,1479,1479,1479
BEGIN DESCRIPTION:
Mapping XS d591b951
END DESCRIPTION:
XS GIS Cut Line= 2
      1679216.69      7044914.81      1679878.59      7046748.61
#Sta/Elev= 30
  4071.7 1415.87  4111.6 1411.59  4167.6 1393.75  4229.0 1384.71  4298.4 1360.36
  4394.0 1336.97  4564.1 1337.02  4637.2 1332.21  4642.5 1328.55  4723.6 1334.55
  4776.8 1327.01  4798.0 1327.93  4815.9 1320.07  4829.9 1321.19  4851.9 1333.45
  4883.1 1335.10  4907.9 1333.60  4933.3 1315.85  4957.5 1313.53  4963.8 1303.47
  4971.3 1302.47  5053.8 1303.47  5086.7 1318.16  5168.0 1323.25  5254.8 1339.69
  5525.5 1344.54  5637.6 1367.35  5680.4 1386.92  5712.3 1393.77  6021.3 1416.72
#Mann=3,-1,0
  4071.7    0.05       0  4963.8    0.03       0  5053.8    0.05       0
Bank Sta=4963.8,5053.8
Exp/Cntr=0.3,0.1

Type RM Length L Ch R = 1,125230,1650,1650,1650
BEGIN DESCRIPTION:
Mapping XS ea26ec7e
END DESCRIPTION:
XS GIS Cut Line= 2
      1677762.71      7045826.30      1679846.05      7047399.66
#Sta/Elev= 30
  4175.6 1528.44  4291.9 1526.89  4350.1 1518.10  4414.7 1486.71  4470.9 1479.93
  4535.4 1461.93  4627.3 1415.43  4706.1 1371.69  4935.0 1324.68  4985.0 1311.03
  4992.5 1301.37  4996.2 1300.37  5037.5 1301.37  5052.2 1304.67  5070.3 1303.97
  5113.7 1316.59  5213.9 1322.80  5256.2 1317.73  5492.8 1338.97  5519.9 1339.45
  5528.2 1333.72  5563.6 1339.77  5707.2 1341.72  5750.5 1349.85  5832.2 1376.84
  5848.7 1383.63  5934.1 1391.93  6233.8 1400.71  6591.7 1426.97  6786.3 1429.57
#Mann=8,-1,0
  4175.6    0.05       0  4627.3    0.12       0  4992.5    0.07       0
  5037.5    0.12       0  5052.2    0.12       0  5113.7    0.05       0
  5750.5    0.12       0  5832.2    0.05       0
Bank Sta=4992.5,5037.5
Exp/Cntr=0.3,0.1

Type RM Length L Ch R = 1,123580,1678,1678,1678
BEGIN DESCRIPTION:
Clear Fork Brazos Rv 32.0
END DESCRIPTION:
XS GIS Cut Line= 3
      1676954.97      7047287.99      1677955.00      7047788.00
      1678455.03      7047788.00
#Sta/Elev= 30
  3876.7 1495.91  4024.9 1496.02  4092.0 1490.31  4226.1 1458.10  4254.6 1442.20
  4349.7 1388.44  4399.4 1357.19  4421.8 1348.84  4533.6 1336.28  4581.6 1321.27
  4582.4 1321.30  4645.4 1319.88  4681.7 1313.61  4712.5 1319.44  4748.8 1314.35
  4800.9 1317.14  4812.0 1318.07  4910.1 1317.00  4964.0 1310.13  4981.6 1300.82
  4987.6 1299.82  5053.6 1300.82  5074.8 1311.98  5104.8 1318.52  5114.8 1327.68
  5154.8 1335.60  5215.2 1337.69  5324.8 1341.87  5413.3 1354.17  5494.8 1373.39
#Mann=12,-1,0
  3876.7    0.05       0  4254.6    0.12       0  4349.7    0.05       0
  4581.6    0.12       0  4582.4    0.05       0  4800.9    0.12       0
  4812.0    0.05       0  4910.1    0.12       0  4981.6    0.07       0
  5053.6    0.12       0  5215.2    0.05       0  5413.3    0.12       0
Bank Sta=4981.6,5053.6
Exp/Cntr=0.3,0.1

Type RM Length L Ch R = 1,121902,2192,2192,2192
BEGIN DESCRIPTION:
Mapping XS 9ce225c4
END DESCRIPTION:
XS GIS Cut Line= 2
      1676894.68      7049558.92      1679161.18      7048734.73
#Sta/Elev= 30
  4188.5 1495.83  4383.5 1467.67  4439.4 1451.21  4500.6 1442.95  4561.8 1418.30
  4671.2 1351.24  4698.8 1342.40  4774.1 1331.58  4837.9 1335.26  4891.1 1319.60
  4944.3 1317.68  4955.0 1315.72  4968.8 1300.13  4975.5 1300.01  4984.5 1299.01
  5083.5 1300.01  5093.3 1309.78  5141.7 1335.46  5190.2 1336.54  5359.3 1335.37
  5498.1 1339.79  5593.4 1347.13  5648.3 1360.55  5704.8 1365.85  5849.3 1371.60
  5899.8 1380.67  5967.0 1384.90  5971.1 1385.04  6083.4 1392.91  6600.2 1410.47
#Mann=9,-1,0
  4188.5    0.05       0  4671.2    0.12       0  4975.5    0.07       0
  5083.5    0.12       0  5190.2    0.05       0  5648.3    0.12       0
  5704.8    0.05       0  5967.0    0.12       0  5971.1    0.05       0
Bank Sta=4975.5,5083.5
Exp/Cntr=0.3,0.1

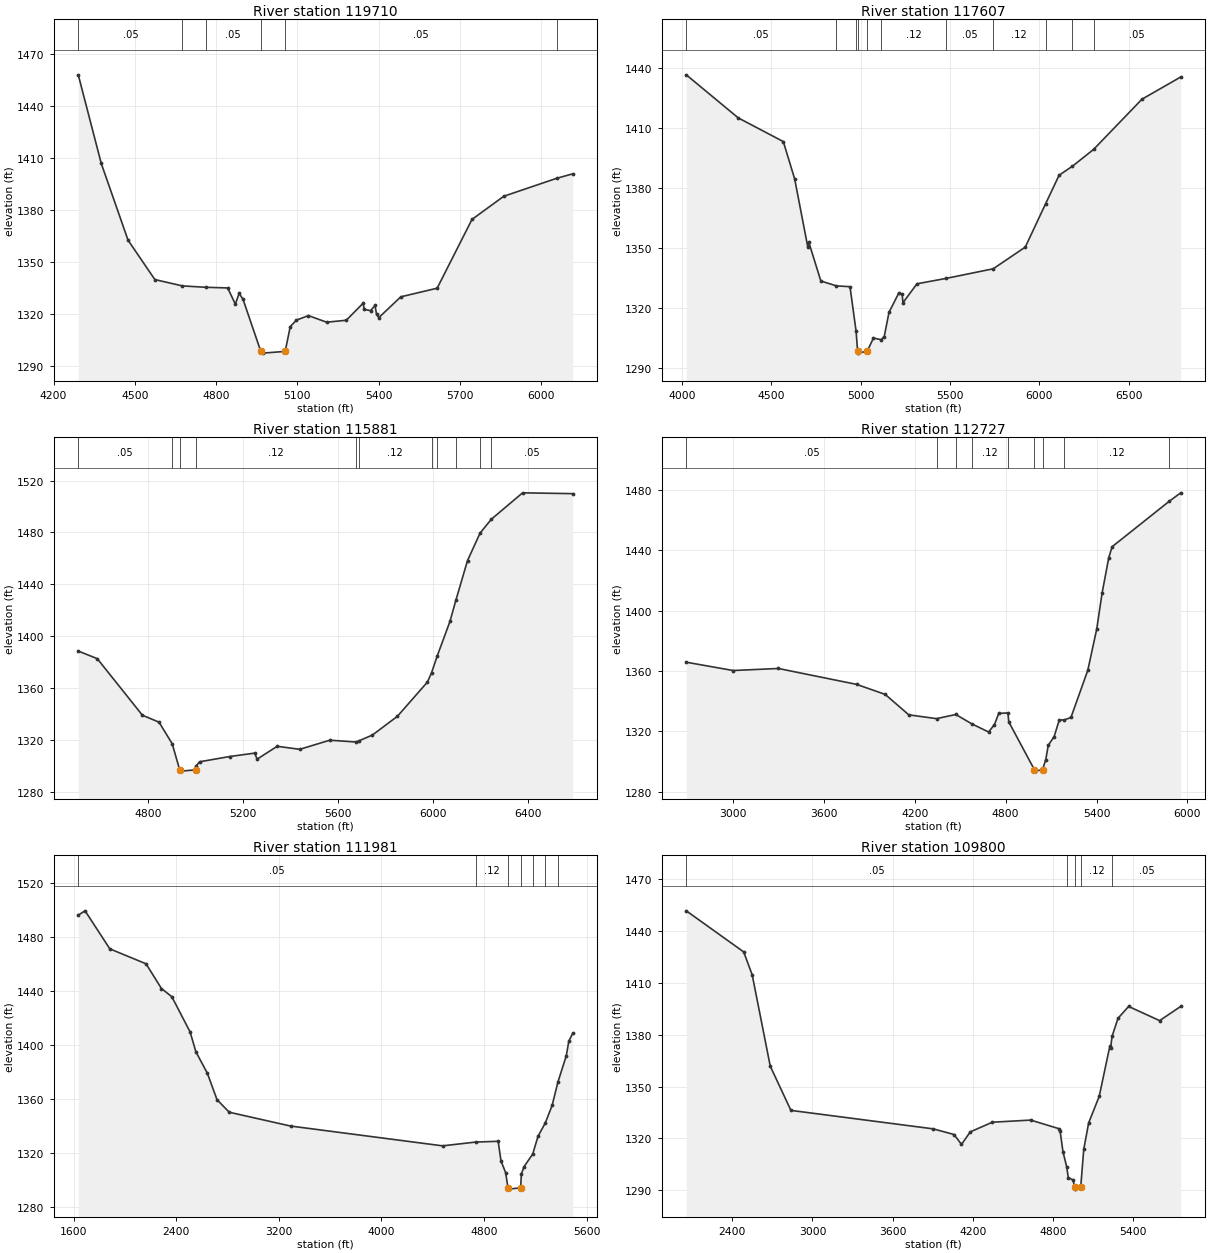
Type RM Length L Ch R = 1,119710,2103,2103,2103
BEGIN DESCRIPTION:
Clear Fork Brazos Rv 31.0
END DESCRIPTION:
XS GIS Cut Line= 3
      1678605.02      7051137.98      1679105.00      7050638.00
      1679605.00      7049638.01
#Sta/Elev= 30
  4291.2 1458.06  4376.0 1406.99  4475.0 1362.68  4574.0 1339.97  4675.8 1336.32
  4762.0 1335.52  4842.7 1335.15  4871.0 1325.84  4885.1 1332.04  4899.3 1328.64
  4965.0 1298.55  4972.5 1297.55  5055.0 1298.55  5073.7 1312.79  5096.1 1316.55
  5140.8 1319.20  5207.9 1315.39  5280.6 1316.51  5342.1 1326.24  5347.7 1322.77
  5370.0 1322.04  5386.8 1325.03  5392.4 1319.85  5400.8 1318.05  5481.8 1330.02
  5616.0 1335.00  5744.6 1374.66  5862.0 1388.03  6057.7 1398.40  6116.3 1400.95
#Mann=6,-1,0
  4291.2    0.05       0  4675.8    0.12       0  4762.0    0.05       0
  4965.0    0.07       0  5055.0    0.05       0  6057.7    0.05       0
Bank Sta=4965,5055
Exp/Cntr=0.3,0.1

Type RM Length L Ch R = 1,117607,1726,1726,1726
BEGIN DESCRIPTION:
Mapping XS 193bcc59
END DESCRIPTION:
XS GIS Cut Line= 2
      1681139.66      7051906.39      1680775.07      7049163.31
#Sta/Elev= 30
  4023.2 1436.63  4314.1 1415.05  4566.3 1403.19  4629.8 1384.49  4703.1 1350.47
  4708.1 1353.00  4776.4 1333.35  4863.1 1330.90  4939.6 1330.49  4973.8 1308.08
  4982.0 1298.21  4986.5 1297.21  5036.0 1298.21  5070.7 1304.75  5114.1 1303.94
  5131.2 1305.52  5157.8 1317.63  5211.9 1327.20  5231.0 1326.86  5236.1 1322.49
  5314.4 1331.94  5478.9 1334.67  5740.9 1339.46  5920.6 1350.33  6034.0 1371.98
  6109.8 1386.33  6184.6 1390.86  6302.6 1399.24  6573.8 1424.43  6790.4 1435.53
#Mann=11,-1,0
  4023.2    0.05       0  4863.1    0.12       0  4973.8    0.05       0
  4982.0    0.05       0  5036.0    0.05       0  5114.1    0.12       0
  5478.9    0.05       0  5740.9    0.12       0  6034.0    0.05       0
  6184.6    0.12       0  6302.6    0.05       0
Bank Sta=4982,5036
Exp/Cntr=0.3,0.1

Type RM Length L Ch R = 1,115881,3154,3154,3154
BEGIN DESCRIPTION:
Clear Fork Brazos Rv 30.0
END DESCRIPTION:
XS GIS Cut Line= 3
      1682655.00      7051237.98      1682655.00      7050738.00
      1683154.99      7049238.02
#Sta/Elev= 30
  4505.4 1388.42  4585.4 1382.56  4775.4 1338.89  4845.4 1333.54  4900.8 1316.87
  4932.3 1296.75  4938.3 1295.75  5000.3 1296.75  5002.9 1299.97  5015.9 1302.95
  5142.4 1307.01  5247.8 1309.64  5258.4 1305.01  5342.7 1314.93  5437.6 1312.57
  5564.1 1319.62  5674.3 1318.22  5686.3 1319.10  5743.2 1323.57  5848.7 1338.05
  5975.1 1364.49  5992.3 1371.58  6016.0 1384.44  6070.0 1411.33  6094.6 1427.48
  6143.8 1458.25  6196.8 1479.52  6244.2 1490.18  6375.7 1510.55  6586.5 1509.91
#Mann=11,-1,0
  4505.4    0.05       0  4900.8    0.12       0  4932.3    0.07       0
  5000.3    0.12       0  5674.3    0.05       0  5686.3    0.12       0
  5992.3    0.05       0  6016.0    0.12       0  6094.6    0.05       0
  6196.8    0.12       0  6244.2    0.05       0
Bank Sta=4932.3,5000.3
Exp/Cntr=0.3,0.1

Type RM Length L Ch R = 1,112727,746,746,746
BEGIN DESCRIPTION:
Mapping XS 27fc9157
END DESCRIPTION:
XS GIS Cut Line= 2
      1684229.09      7052868.60      1685718.85      7049965.09
#Sta/Elev= 30
  2692.1 1365.85  3001.3 1360.35  3299.7 1361.70  3816.8 1351.17  4005.3 1344.53
  4160.7 1331.02  4343.9 1328.50  4471.0 1331.25  4576.8 1325.05  4687.6 1319.66
  4726.4 1324.61  4754.2 1331.94  4815.1 1332.32  4820.8 1326.35  4989.6 1294.77
  4994.1 1293.77  5043.6 1294.77  5064.9 1301.41  5081.5 1310.90  5120.3 1316.68
  5154.2 1327.66  5187.2 1327.63  5231.2 1329.30  5342.2 1360.45  5401.5 1387.90
  5436.6 1411.55  5480.9 1435.12  5503.1 1442.29  5881.3 1472.46  5955.5 1477.94
#Mann=9,-1,0
  2692.1    0.05       0  4343.9    0.12       0  4471.0    0.05       0
  4576.8    0.12       0  4815.1    0.05       0  4989.6    0.05       0
  5043.6    0.05       0  5187.2    0.12       0  5881.3    0.05       0
Bank Sta=4989.6,5043.6
Exp/Cntr=0.3,0.1

Type RM Length L Ch R = 1,111981,2181,2181,2181
BEGIN DESCRIPTION:
Clear Fork Brazos Rv 29.0
END DESCRIPTION:
XS GIS Cut Line= 3
      1684304.99      7054338.02      1685805.00      7051338.00
      1685805.00      7050838.03
#Sta/Elev= 30
  1636.4 1496.18  1689.5 1499.34  1882.4 1471.23  2164.7 1460.17  2284.9 1441.91
  2365.9 1435.81  2508.5 1409.74  2553.2 1395.14  2642.7 1379.25  2718.1 1359.69
  2813.2 1350.43  3291.1 1340.21  4476.2 1325.57  4733.8 1328.36  4909.5 1328.94
  4931.8 1314.41  4968.2 1305.68  4985.8 1294.57  4994.1 1293.57  5084.8 1294.57
  5090.5 1304.69  5110.5 1310.06  5179.0 1319.49  5220.5 1332.72  5276.8 1342.42
  5330.5 1355.49  5374.6 1372.46  5440.5 1392.13  5460.5 1403.01  5490.5 1408.74
#Mann=7,-1,0
  1636.4    0.05       0  4733.8    0.12       0  4985.8    0.03       0
  5084.8    0.12       0  5179.0    0.12       0  5276.8    0.05       0
  5374.6    0.12       0
Bank Sta=4985.8,5084.8
Exp/Cntr=0.3,0.1

Type RM Length L Ch R = 1,109800,2020,2020,2020
BEGIN DESCRIPTION:
Mapping XS 080ad632
END DESCRIPTION:
XS GIS Cut Line= 3
      1684806.76      7054084.67      1685262.80      7053537.42
      1688059.84      7052488.53
#Sta/Elev= 30
  2056.1 1451.57  2485.4 1427.84  2549.2 1414.62  2684.5 1361.75  2839.1 1336.19
  3902.9 1325.53  4060.2 1322.23  4115.4 1316.51  4181.2 1323.77  4346.8 1329.36
  4633.4 1330.59  4842.7 1325.66  4853.4 1324.31  4874.8 1312.30  4902.4 1303.63
  4914.6 1297.25  4950.2 1296.04  4962.4 1291.67  4966.2 1290.67  5007.4 1291.67
  5030.3 1313.66  5067.0 1328.97  5146.0 1344.30  5226.1 1373.53  5231.4 1372.42
  5242.2 1378.99  5286.6 1389.43  5366.0 1396.29  5598.1 1388.09  5755.7 1396.30
#Mann=5,-1,0
  2056.1    0.05       0  4902.4    0.12       0  4962.4    0.07       0
  5007.4    0.12       0  5242.2    0.05       0
Bank Sta=4962.4,5007.4
Exp/Cntr=0.3,0.1

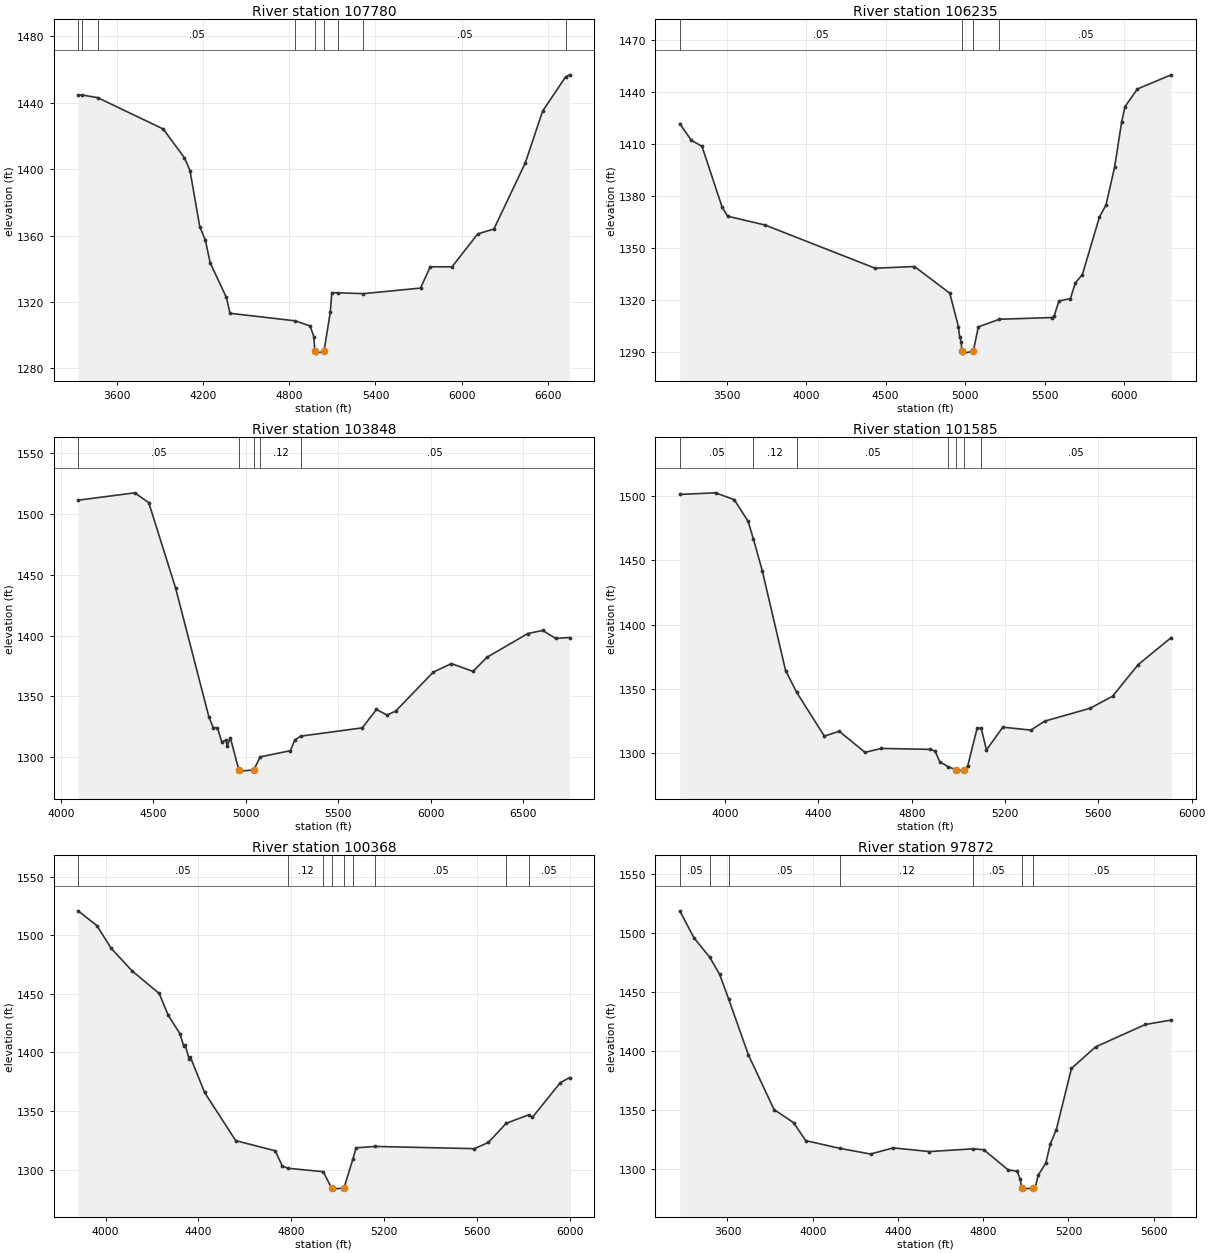
Type RM Length L Ch R = 1,107780,1545,1545,1545
BEGIN DESCRIPTION:
Mapping XS 169fd14c
END DESCRIPTION:
XS GIS Cut Line= 3
      1684945.90      7054213.87      1685629.45      7054148.77
      1688255.36      7054897.48
#Sta/Elev= 30
  3332.3 1444.60  3360.5 1444.65  3468.6 1443.05  3924.1 1424.17  4071.2 1406.87
  4110.2 1399.15  4177.9 1365.41  4216.9 1357.30  4250.7 1343.52  4362.6 1322.85
  4388.7 1313.17  4843.0 1308.62  4945.5 1305.50  4971.0 1299.17  4978.7 1290.18
  4984.0 1289.18  5041.7 1290.18  5085.4 1313.67  5096.5 1325.64  5141.3 1325.49
  5316.6 1325.01  5713.2 1328.36  5780.9 1341.19  5931.8 1341.15  6111.4 1361.00
  6223.3 1363.93  6441.9 1403.80  6562.0 1434.95  6721.9 1455.58  6749.5 1456.80
#Mann=9,-1,0
  3332.3    0.05       0  3360.5    0.12       0  3468.6    0.05       0
  4843.0    0.12       0  4978.7    0.07       0  5041.7    0.12       0
  5141.3    0.12       0  5316.6    0.05       0  6721.9    0.12       0
Bank Sta=4978.7,5041.7
Exp/Cntr=0.3,0.1

Type RM Length L Ch R = 1,106235,2387,2387,2387
BEGIN DESCRIPTION:
Mapping XS 1b08c5b0
END DESCRIPTION:
XS GIS Cut Line= 3
      1684294.80      7055125.33      1687126.85      7056232.11
      1687168.98      7056263.71
#Sta/Elev= 30
  3204.2 1421.51  3277.2 1411.90  3344.0 1408.44  3470.0 1373.54  3505.2 1368.11
  3741.2 1363.03  4433.9 1338.10  4681.0 1339.10  4903.6 1323.72  4957.9 1304.48
  4965.2 1298.67  4975.9 1295.59  4979.5 1290.12  4985.5 1289.12  5051.5 1290.12
  5083.3 1304.26  5216.5 1308.67  5545.0 1309.64  5560.8 1310.56  5590.6 1319.18
  5663.1 1320.58  5693.9 1329.66  5738.2 1334.45  5845.6 1367.63  5886.7 1374.54
  5941.0 1396.37  5985.2 1422.37  6006.6 1431.36  6084.8 1441.54  6297.5 1449.69
#Mann=4,-1,0
  3204.2    0.05       0  4979.5    0.05       0  5051.5    0.05       0
  5216.5    0.05       0
Bank Sta=4979.5,5051.5
Exp/Cntr=0.3,0.1

Type RM Length L Ch R = 1,103848,2263,2263,2263
BEGIN DESCRIPTION:
Mapping XS 3473c4f4
END DESCRIPTION:
XS GIS Cut Line= 2
      1684229.73      7058206.93      1686659.78      7057132.93
#Sta/Elev= 30
  4093.7 1511.43  4400.2 1517.48  4475.6 1509.38  4620.8 1439.02  4800.4 1333.14
  4823.7 1324.26  4847.0 1323.91  4870.3 1312.43  4893.6 1313.92  4899.0 1308.67
  4916.9 1315.77  4962.4 1289.34  4969.1 1288.34  5043.4 1289.34  5077.8 1300.04
  5241.7 1305.19  5265.0 1314.04  5297.1 1317.14  5630.1 1323.98  5706.3 1339.11
  5763.8 1334.54  5810.4 1337.76  6013.2 1369.80  6111.9 1376.91  6228.4 1370.42
  6303.8 1382.05  6524.4 1401.61  6605.3 1404.18  6675.2 1397.59  6750.5 1398.33
#Mann=5,-1,0
  4093.7    0.05       0  4962.4    0.03       0  5043.4    0.05       0
  5077.8    0.12       0  5297.1    0.05       0
Bank Sta=4962.4,5043.4
Exp/Cntr=0.3,0.1

Type RM Length L Ch R = 1,101585,1217,1217,1217
BEGIN DESCRIPTION:
Mapping XS 21dc7979
END DESCRIPTION:
XS GIS Cut Line= 2
      1686862.74      7059731.03      1686751.63      7057626.86
#Sta/Elev= 30
  3805.3 1501.14  3958.5 1502.39  4038.7 1497.10  4098.7 1480.12  4120.8 1466.55
  4158.8 1441.99  4259.0 1364.25  4306.9 1347.20  4425.2 1313.28  4489.3 1317.01
  4599.4 1300.66  4669.5 1303.71  4879.8 1302.98  4899.9 1301.67  4919.9 1293.42
  4955.1 1289.58  4990.0 1287.06  4993.0 1286.06  5026.0 1287.06  5040.1 1290.30
  5080.1 1319.36  5097.7 1319.47  5120.2 1302.49  5190.3 1320.23  5310.4 1317.96
  5370.0 1324.90  5564.9 1334.95  5660.9 1344.29  5771.1 1368.94  5912.4 1389.86
#Mann=7,-1,0
  3805.3    0.05       0  4120.8    0.12       0  4306.9    0.05       0
  4955.1    0.12       0  4990.0    0.07       0  5026.0    0.12       0
  5097.7    0.05       0
Bank Sta=4990,5026
Exp/Cntr=0.3,0.1

Type RM Length L Ch R = 1,100368,2496,2496,2496
BEGIN DESCRIPTION:
Clear Fork Brazos Rv 26.0
END DESCRIPTION:
XS GIS Cut Line= 3
      1687505.01      7059587.99      1688005.00      7058588.00
      1688005.00      7057588.02
#Sta/Elev= 30
  3881.8 1520.91  3962.8 1508.30  4024.3 1488.90  4113.8 1469.74  4231.2 1450.35
  4270.3 1431.70  4320.6 1416.02  4337.4 1405.13  4343.0 1406.59  4359.7 1394.67
  4365.3 1396.20  4426.8 1365.86  4561.0 1324.70  4731.5 1315.99  4762.2 1302.85
  4787.2 1301.08  4938.4 1298.18  4973.8 1284.29  4978.3 1283.29  5027.8 1284.29
  5066.5 1309.38  5079.8 1318.59  5163.4 1319.73  5589.8 1317.85  5649.8 1323.15
  5726.8 1339.52  5824.6 1346.81  5839.8 1344.59  5959.8 1374.17  5999.8 1378.52
#Mann=9,-1,0
  3881.8    0.05       0  4787.2    0.12       0  4938.4    0.05       0
  4973.8    0.03       0  5027.8    0.05       0  5066.5    0.12       0
  5163.4    0.05       0  5726.8    0.12       0  5824.6    0.05       0
Bank Sta=4973.8,5027.8
Exp/Cntr=0.3,0.1

Type RM Length L Ch R = 1,97872,1393,1393,1393
BEGIN DESCRIPTION:
Mapping XS a6a1de22
END DESCRIPTION:
XS GIS Cut Line= 2
      1690534.00      7058413.13      1689004.00      7056687.81
#Sta/Elev= 30
  3376.1 1518.41  3442.8 1495.52  3516.6 1479.09  3563.2 1464.63  3605.0 1443.96
  3697.8 1396.59  3818.3 1350.21  3910.3 1339.05  3967.1 1323.85  4129.9 1317.21
  4271.6 1312.52  4377.8 1317.73  4547.6 1314.59  4751.4 1316.91  4802.6 1316.17
  4916.4 1299.15  4959.0 1297.88  4973.3 1291.44  4980.1 1283.80  4984.6 1282.80
  5034.1 1283.80  5043.5 1283.81  5057.7 1294.55  5093.7 1304.80  5114.6 1321.00
  5143.0 1333.27  5214.0 1384.97  5327.0 1403.21  5561.2 1422.21  5682.1 1425.99
#Mann=7,-1,0
  3376.1    0.05       0  3516.6    0.12       0  3605.0    0.05       0
  4129.9    0.12       0  4751.4    0.05       0  4980.1    0.05       0
  5034.1    0.05       0
Bank Sta=4980.1,5034.1
Exp/Cntr=0.3,0.1

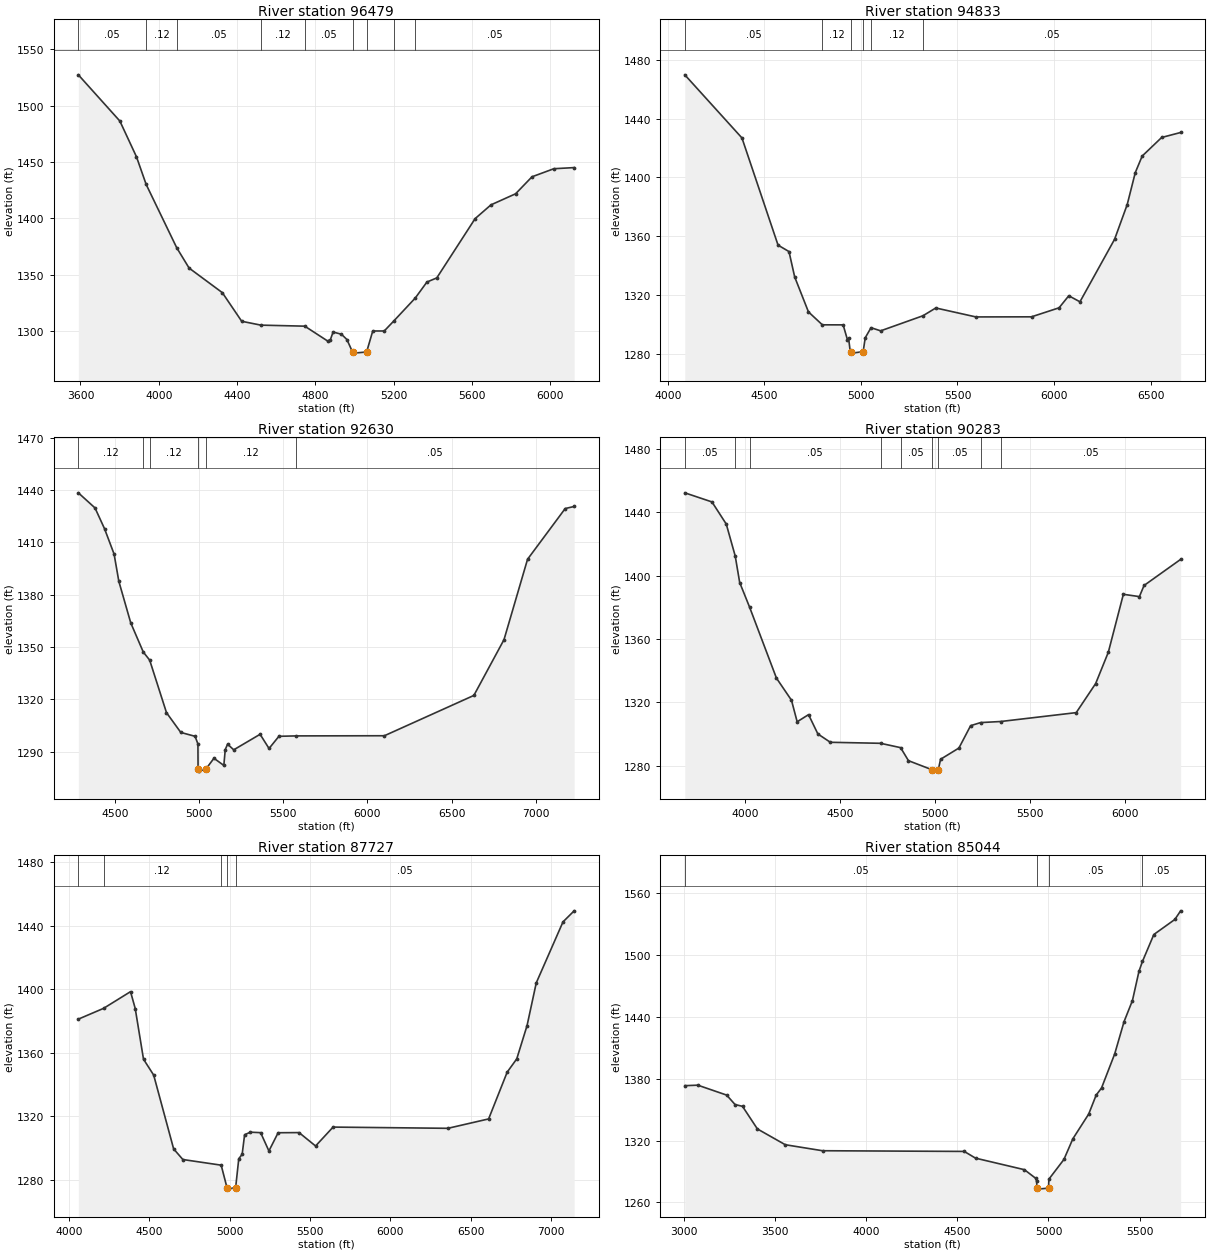
Type RM Length L Ch R = 1,96479,1646,1646,1646
BEGIN DESCRIPTION:
Clear Fork Brazos Rv 25.0
END DESCRIPTION:
XS GIS Cut Line= 3
      1691605.01      7057538.01      1690605.00      7056538.00
      1690104.98      7055537.97
#Sta/Elev= 30
  3589.0 1527.16  3801.1 1486.25  3886.0 1454.58  3935.4 1430.14  4091.6 1374.05
  4154.7 1356.10  4324.4 1334.34  4423.4 1308.99  4521.2 1305.58  4745.4 1304.67
  4861.8 1291.57  4875.9 1292.53  4890.1 1299.46  4932.5 1297.56  4960.8 1292.83
  4989.3 1281.80  4995.3 1280.80  5061.3 1281.80  5092.7 1300.40  5151.4 1300.41
  5198.9 1309.02  5309.7 1329.55  5369.4 1343.74  5419.7 1347.39  5615.4 1399.85
  5696.4 1412.05  5822.2 1421.85  5906.0 1436.90  6017.8 1444.05  6121.3 1445.03
#Mann=9,-1,0
  3589.0    0.05       0  3935.4    0.12       0  4091.6    0.05       0
  4521.2    0.12       0  4745.4    0.05       0  4989.3    0.05       0
  5061.3    0.05       0  5198.9    0.12       0  5309.7    0.05       0
Bank Sta=4989.3,5061.3
Exp/Cntr=0.3,0.1

Type RM Length L Ch R = 1,94833,2203,2203,2203
BEGIN DESCRIPTION:
Mapping XS 0d3257d7
END DESCRIPTION:
XS GIS Cut Line= 2
      1692519.64      7056546.77      1691033.24      7054452.79
#Sta/Elev= 30
  4087.9 1469.71  4383.9 1426.78  4570.9 1353.87  4627.5 1349.50  4657.0 1332.25
  4728.3 1308.47  4800.3 1299.68  4908.0 1299.65  4930.1 1289.59  4936.2 1290.55
  4944.8 1281.43  4948.6 1281.43  4953.8 1280.43  5011.6 1281.43  5022.4 1290.87
  5052.3 1297.72  5102.3 1295.59  5321.6 1305.86  5387.7 1311.14  5595.6 1305.05
  5883.5 1305.12  6026.2 1311.25  6076.6 1319.44  6134.4 1315.34  6314.0 1357.91
  6379.2 1381.49  6421.0 1403.22  6456.7 1414.46  6557.6 1427.10  6655.8 1430.49
#Mann=6,-1,0
  4087.9    0.05       0  4800.3    0.12       0  4948.6    0.03       0
  5011.6     0.1       0  5052.3    0.12       0  5321.6    0.05       0
Bank Sta=4948.6,5011.6
Exp/Cntr=0.3,0.1

Type RM Length L Ch R = 1,92630,2347,2347,2347
BEGIN DESCRIPTION:
Clear Fork Brazos Rv 24.0
END DESCRIPTION:
XS GIS Cut Line= 3
      1693805.03      7054688.03      1693305.00      7054188.00
      1691305.02      7053188.01
#Sta/Elev= 30
  4283.9 1438.44  4382.9 1429.77  4439.5 1417.83  4496.1 1403.32  4524.4 1387.63
  4595.1 1363.81  4669.5 1347.09  4707.4 1342.46  4807.2 1312.32  4892.1 1300.98
  4976.9 1298.75  4993.8 1294.38  4994.7 1279.78  4998.5 1278.78  5039.7 1279.78
  5088.9 1286.16  5147.6 1282.05  5156.0 1291.15  5169.9 1294.25  5206.3 1291.00
  5362.8 1299.91  5415.9 1291.77  5474.6 1298.76  5577.3 1298.99  6100.7 1299.08
  6631.8 1322.21  6810.7 1354.21  6950.4 1400.32  7174.0 1429.43  7227.1 1430.61
#Mann=6,-1,0
  4283.9    0.12       0  4669.5    0.05       0  4707.4    0.12       0
  4994.7    0.07       0  5039.7    0.12       0  5577.3    0.05       0
Bank Sta=4994.7,5039.7
Exp/Cntr=0.3,0.1

Type RM Length L Ch R = 1,90283,2556,2556,2556
BEGIN DESCRIPTION:
Mapping XS 1b9ac7ca
END DESCRIPTION:
XS GIS Cut Line= 2
      1694668.08      7052477.77      1692238.78      7051534.24
#Sta/Elev= 30
  3685.1 1452.31  3827.9 1446.56  3903.0 1432.60  3950.1 1412.43  3973.6 1395.68
  4026.0 1380.01  4166.8 1335.32  4245.8 1321.36  4275.7 1307.75  4335.5 1312.26
  4384.6 1300.06  4450.1 1294.80  4714.3 1294.16  4819.4 1291.41  4860.7 1283.19
  4981.8 1277.59  4984.8 1276.59  5017.8 1277.59  5029.4 1284.07  5125.9 1291.17
  5187.4 1305.29  5240.0 1307.24  5345.2 1307.92  5742.5 1313.53  5844.7 1331.90
  5911.2 1351.66  5990.2 1388.24  6074.5 1386.78  6099.0 1393.82  6291.2 1410.28
#Mann=9,-1,0
  3685.1    0.05       0  3950.1    0.12       0  4026.0    0.05       0
  4714.3    0.12       0  4819.4    0.05       0  4981.8    0.05       0
  5017.8    0.05       0  5240.0    0.12       0  5345.2    0.05       0
Bank Sta=4981.8,5017.8
Exp/Cntr=0.3,0.1

Type RM Length L Ch R = 1,87727,2683,2683,2683
BEGIN DESCRIPTION:
Mapping XS afe21804
END DESCRIPTION:
XS GIS Cut Line= 2
      1695178.07      7050394.44      1692584.71      7048723.40
#Sta/Elev= 30
  4057.7 1381.23  4214.5 1388.01  4382.5 1398.54  4411.7 1387.92  4463.2 1356.03
  4526.6 1346.00  4650.7 1299.56  4708.1 1292.87  4946.5 1289.32  4982.5 1275.24
  4987.0 1274.24  5036.5 1275.24  5056.0 1293.37  5077.1 1296.18  5092.3 1308.49
  5128.6 1310.08  5192.0 1309.78  5243.5 1298.27  5300.9 1309.73  5431.0 1309.83
  5533.9 1301.39  5642.8 1313.29  6357.3 1312.52  6610.6 1318.43  6726.1 1347.88
  6785.6 1356.22  6849.6 1377.13  6907.0 1404.06  7073.4 1442.46  7142.8 1449.41
#Mann=5,-1,0
  4057.7    0.05       0  4214.5    0.12       0  4946.5    0.05       0
  4982.5    0.03       0  5036.5    0.05       0
Bank Sta=4982.5,5036.5
Exp/Cntr=0.3,0.1

Type RM Length L Ch R = 1,85044,2993,2993,2993
BEGIN DESCRIPTION:
Mapping XS db783ad6
END DESCRIPTION:
XS GIS Cut Line= 2
      1695677.21      7049624.07      1695004.46      7046987.34
#Sta/Elev= 30
  3004.0 1373.36  3075.5 1373.85  3233.8 1364.21  3279.8 1355.05  3320.7 1353.30
  3402.4 1331.36  3555.5 1316.02  3759.9 1310.19  4537.7 1309.52  4599.6 1302.99
  4867.9 1291.78  4929.5 1283.46  4934.6 1280.92  4937.1 1273.91  4942.4 1272.91
  5000.1 1273.91  5002.1 1282.56  5084.7 1301.72  5133.8 1321.80  5220.7 1345.81
  5261.6 1364.18  5291.1 1371.11  5363.3 1404.16  5414.7 1435.52  5460.7 1455.98
  5496.4 1484.27  5515.6 1493.94  5578.2 1520.14  5693.6 1534.78  5725.2 1543.14
#Mann=4,-1,0
  3004.0    0.05       0  4937.1    0.07       0  5000.1    0.05       0
  5515.6    0.05       0
Bank Sta=4937.1,5000.1
Exp/Cntr=0.3,0.1

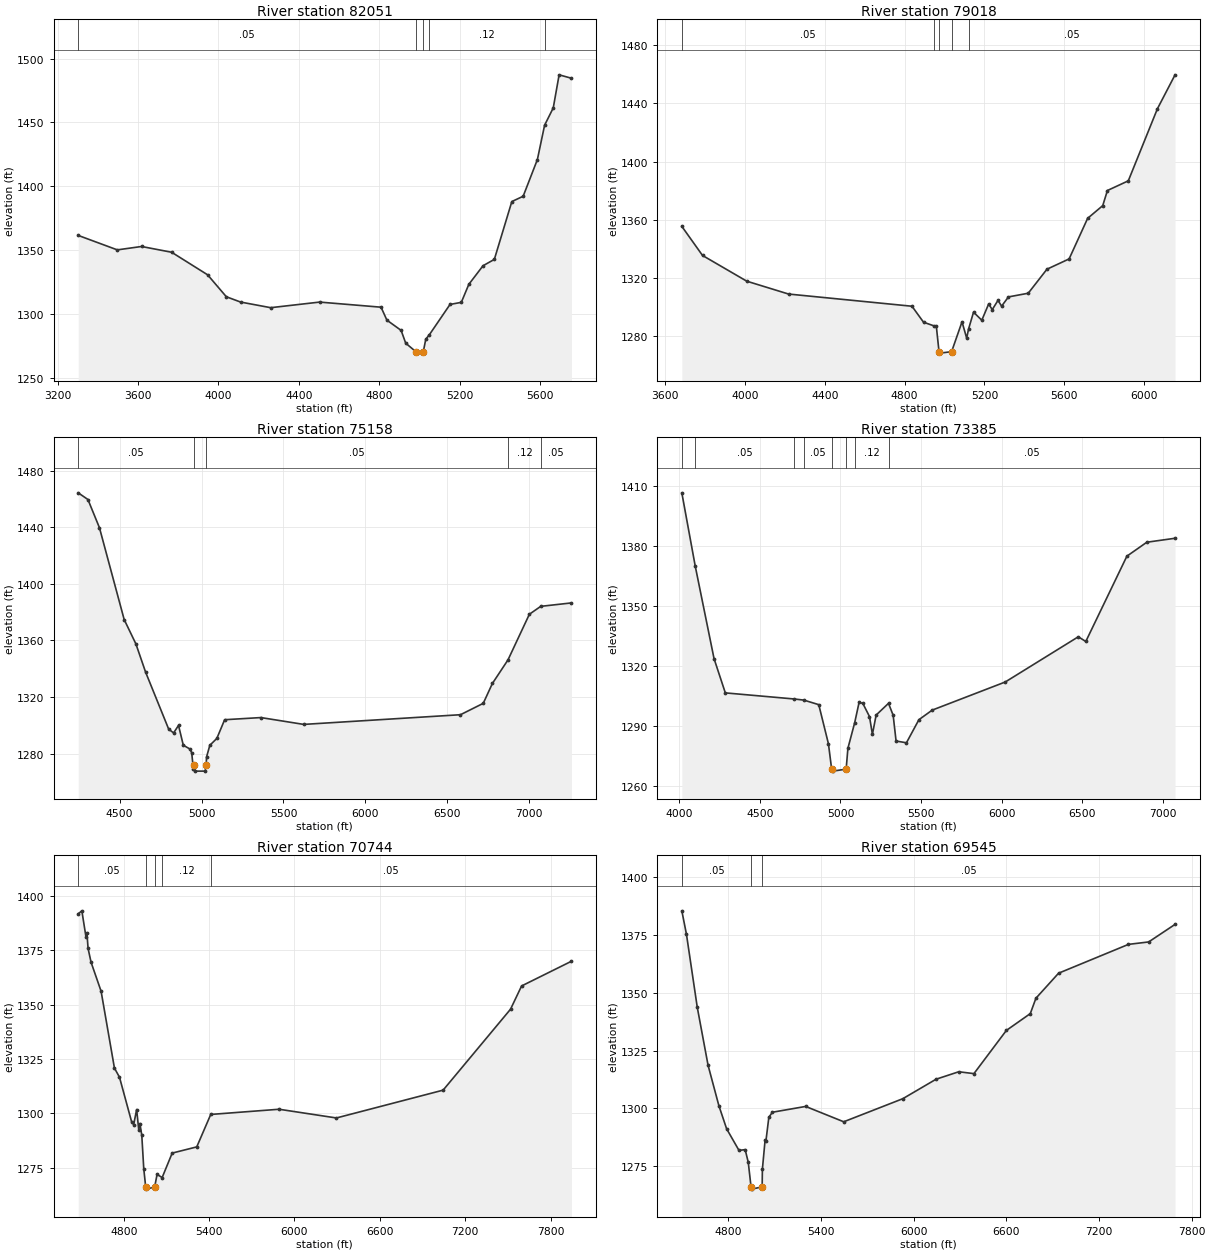
Type RM Length L Ch R = 1,82051,3033,3033,3033
BEGIN DESCRIPTION:
Mapping XS 255f7fdf
END DESCRIPTION:
XS GIS Cut Line= 2
      1696078.68      7049743.39      1698030.94      7048257.50
#Sta/Elev= 30
  3302.5 1361.67  3497.0 1350.36  3617.6 1353.01  3767.3 1348.50  3946.1 1330.87
  4039.3 1313.70  4110.3 1309.55  4260.0 1305.15  4503.2 1309.53  4808.9 1305.53
  4838.0 1295.40  4908.7 1287.40  4931.5 1277.41  4982.9 1270.61  4985.9 1269.61
  5018.9 1270.61  5031.3 1280.48  5049.5 1284.05  5152.0 1307.69  5208.1 1309.32
  5245.5 1323.41  5316.2 1337.96  5372.4 1342.92  5459.4 1388.14  5515.8 1392.30
  5586.5 1420.99  5622.3 1447.81  5665.5 1461.43  5694.6 1487.26  5755.9 1484.59
#Mann=5,-1,0
  3302.5    0.05       0  4982.9    0.05       0  5018.9    0.05       0
  5049.5    0.12       0  5622.3    0.05       0
Bank Sta=4982.9,5018.9
Exp/Cntr=0.3,0.1

Type RM Length L Ch R = 1,79018,3860,3860,3860
BEGIN DESCRIPTION:
Mapping XS 25b19e4d
END DESCRIPTION:
XS GIS Cut Line= 2
      1696295.72      7050991.24      1698561.74      7051977.88
#Sta/Elev= 30
  3683.8 1355.60  3787.5 1335.63  4009.3 1317.95  4218.6 1309.13  4837.1 1300.75
  4894.9 1289.78  4949.5 1287.16  4959.1 1286.96  4972.6 1269.55  4977.9 1268.55
  5035.6 1269.55  5087.8 1290.05  5111.2 1278.80  5120.4 1285.01  5145.5 1296.68
  5186.9 1291.14  5221.3 1302.30  5239.3 1298.43  5268.1 1304.79  5286.1 1300.81
  5320.5 1307.16  5419.6 1309.68  5513.4 1326.18  5624.4 1333.24  5717.2 1361.10
  5792.9 1369.85  5816.4 1380.23  5921.0 1386.87  6067.0 1436.40  6155.3 1459.67
#Mann=5,-1,0
  3683.8    0.05       0  4949.5    0.12       0  4972.6    0.07       0
  5035.6    0.12       0  5120.4    0.05       0
Bank Sta=4972.6,5035.6
Exp/Cntr=0.3,0.1

Type RM Length L Ch R = 1,75158,1773,1773,1773
BEGIN DESCRIPTION:
Mapping XS 795bd222
END DESCRIPTION:
XS GIS Cut Line= 2
      1695405.92      7054268.13      1698400.35      7053964.35
#Sta/Elev= 30
  4247.4 1464.29  4306.8 1459.56  4377.1 1439.60  4527.9 1374.71  4599.4 1357.51
  4658.6 1337.56  4799.3 1297.31  4829.5 1294.55  4859.6 1299.89  4888.7 1285.88
  4930.0 1283.14  4940.0 1280.50  4950.1 1269.22  4956.3 1271.56  4962.3 1267.56
  5022.3 1267.56  5028.3 1271.56  5030.5 1277.49  5050.6 1285.82  5093.3 1290.66
  5141.0 1303.90  5362.2 1305.42  5623.5 1300.59  6580.2 1307.44  6719.1 1315.48
  6774.8 1329.52  6870.2 1346.23  7000.5 1378.46  7069.9 1384.04  7257.2 1386.47
#Mann=5,-1,0
  4247.4    0.05       0  4956.3    0.05       0  5028.3    0.05       0
  6870.2    0.12       0  7069.9    0.05       0
Bank Sta=4956.3,5028.3
Exp/Cntr=0.3,0.1

Type RM Length L Ch R = 1,73385,2641,2641,2641
BEGIN DESCRIPTION:
Clear Fork Brazos Rv 19.0
END DESCRIPTION:
XS GIS Cut Line= 3
      1695904.99      7055638.00      1696905.00      7055638.00
      1698905.03      7055137.99
#Sta/Elev= 30
  4015.2 1406.72  4098.9 1369.88  4215.2 1323.78  4285.2 1306.64  4713.0 1303.59
  4773.0 1303.02  4865.2 1300.75  4925.2 1281.20  4945.2 1268.50  4952.7 1267.50
  5035.2 1268.50  5046.1 1278.91  5088.4 1291.78  5115.7 1301.95  5138.9 1301.36
  5180.1 1294.79  5198.2 1285.89  5221.4 1295.56  5298.1 1301.41  5327.0 1295.45
  5345.1 1282.56  5409.5 1281.68  5486.8 1293.23  5569.3 1298.02  6022.8 1312.09
  6476.3 1334.71  6522.7 1332.35  6777.8 1375.03  6901.5 1382.01  7076.8 1383.99
#Mann=8,-1,0
  4015.2    0.12       0  4098.9    0.05       0  4713.0    0.12       0
  4773.0    0.05       0  4945.2    0.05       0  5035.2    0.05       0
  5088.4    0.12       0  5298.1    0.05       0
Bank Sta=4945.2,5035.2
Exp/Cntr=0.3,0.1

Type RM Length L Ch R = 1,70744,1199,1199,1199
BEGIN DESCRIPTION:
Mapping XS 299eec98
END DESCRIPTION:
XS GIS Cut Line= 3
      1696675.46      7058434.80      1697543.52      7057284.63
      1698920.80      7055798.89
#Sta/Elev= 30
  4480.2 1391.82  4505.9 1393.19  4535.1 1381.08  4541.3 1383.18  4549.6 1375.90
  4570.5 1369.55  4641.2 1356.18  4734.9 1320.83  4770.3 1316.66  4855.6 1296.14
  4870.2 1294.85  4891.0 1301.78  4905.6 1292.58  4913.9 1295.34  4927.2 1289.87
  4941.0 1274.53  4954.6 1266.15  4959.8 1265.15  5017.6 1266.15  5034.6 1271.93
  5070.3 1270.48  5140.8 1281.73  5313.5 1284.58  5411.8 1299.51  5891.9 1301.90
  6295.0 1297.89  7045.1 1310.69  7519.1 1347.94  7596.7 1358.62  7947.1 1369.99
#Mann=5,-1,0
  4480.2    0.05       0  4954.6    0.05       0  5017.6    0.05       0
  5070.3    0.12       0  5411.8    0.05       0
Bank Sta=4954.6,5017.6
Exp/Cntr=0.3,0.1

Type RM Length L Ch R = 1,69545,3923,3923,3923
BEGIN DESCRIPTION:
Clear Fork Brazos Rv 18.0
END DESCRIPTION:
XS GIS Cut Line= 3
      1698155.00      7058637.95      1698155.00      7058138.00
      1699154.99      7055638.03
#Sta/Elev= 30
  4500.1 1385.49  4530.1 1375.36  4600.1 1343.74  4670.1 1318.65  4740.1 1301.16
  4790.1 1291.20  4870.1 1281.86  4910.1 1282.20  4930.1 1276.72  4948.1 1266.11
  4954.1 1265.11  5020.1 1266.11  5021.6 1273.74  5039.1 1286.31  5044.5 1285.94
  5063.3 1296.16  5086.2 1298.37  5301.6 1300.88  5548.0 1294.24  5930.3 1304.22
  6145.7 1312.65  6292.5 1315.88  6390.8 1315.07  6600.8 1333.76  6755.6 1341.03
  6792.0 1347.68  6938.7 1358.51  7391.1 1370.98  7521.7 1372.03  7692.6 1379.63
#Mann=3,-1,0
  4500.1    0.05       0  4948.1    0.03       0  5020.1    0.05       0
Bank Sta=4948.1,5020.1
Exp/Cntr=0.3,0.1