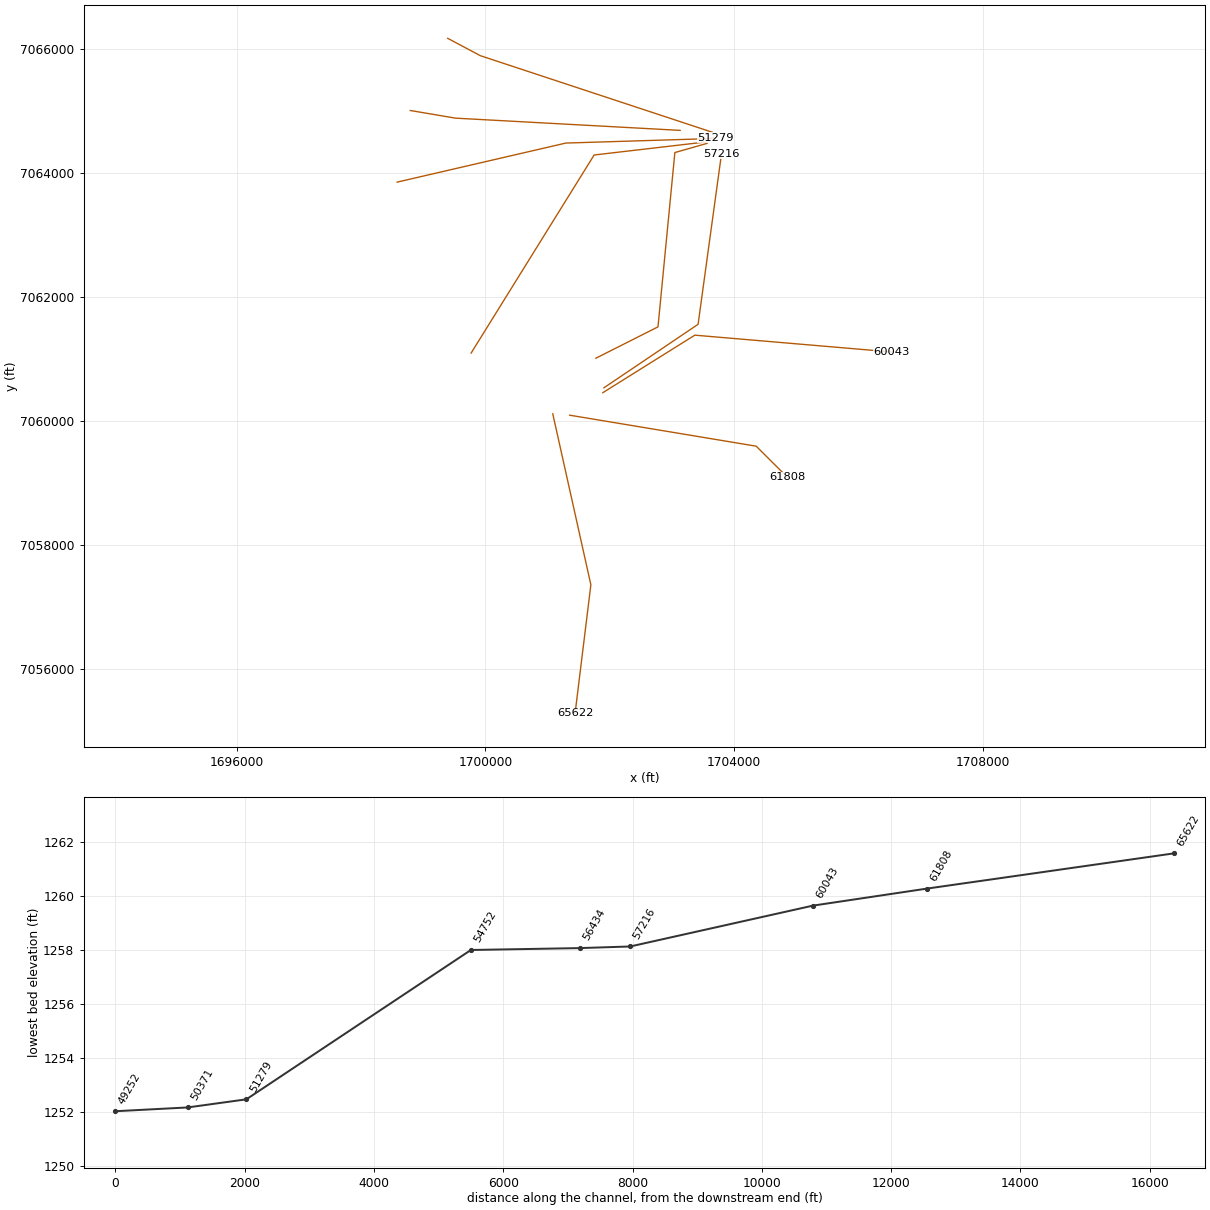
HEC-RAS study Clear Fork Brazos Rv.prj: Clear Fork Brazos Rv Base Level Engineering

--- Clear Fork Brazos Rv.g01 (geometry) --- (continued)

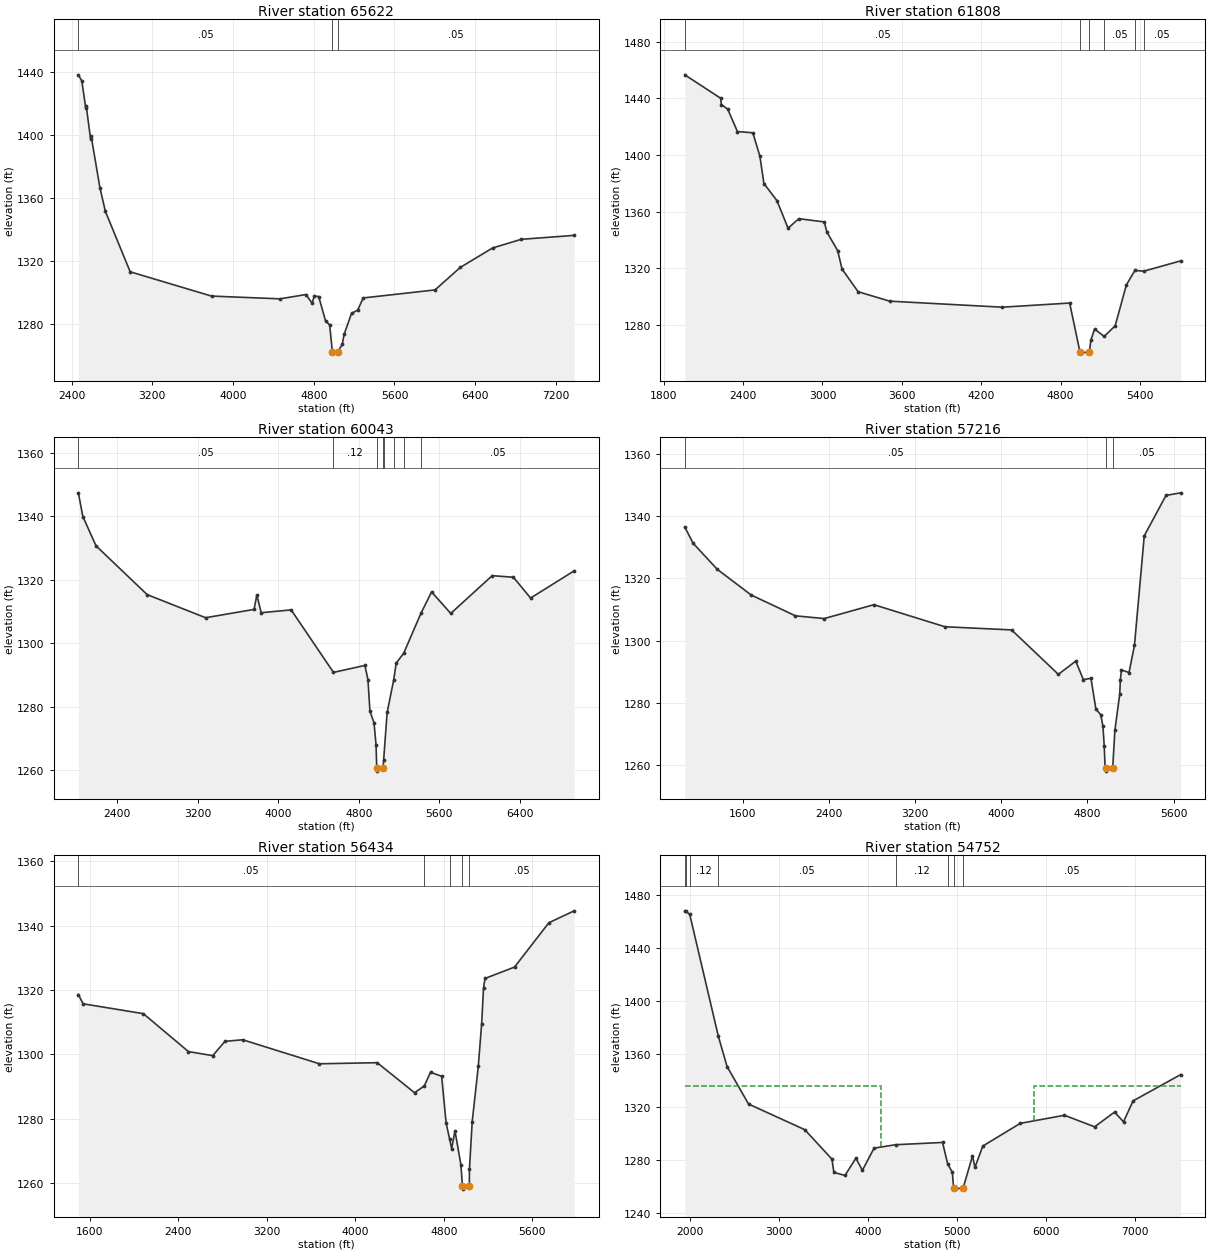
Type RM Length L Ch R = 1,65622,3814,3814,3814
BEGIN DESCRIPTION:
Mapping XS f3daec16
END DESCRIPTION:
XS GIS Cut Line= 3
      1701083.23      7060109.74      1701695.95      7057352.50
      1701442.11      7055277.98
#Sta/Elev= 30
  2466.5 1438.31  2500.9 1434.48  2539.3 1417.53  2544.5 1418.68  2588.0 1397.57
  2593.1 1399.59  2680.2 1366.69  2734.6 1351.59  2980.5 1313.22  3786.5 1297.80
  4465.9 1296.05  4722.0 1298.78  4783.4 1293.29  4805.8 1297.96  4849.3 1297.44
  4916.6 1282.04  4957.6 1279.47  4984.1 1262.57  4988.6 1261.57  5038.1 1262.57
  5082.4 1267.09  5101.0 1273.52  5174.6 1286.83  5234.2 1288.81  5290.7 1296.62
  6002.2 1301.71  6252.6 1316.02  6572.5 1328.35  6857.1 1333.85  7381.0 1336.35
#Mann=3,-1,0
  2466.5    0.05       0  4984.1    0.05       0  5038.1    0.05       0
Bank Sta=4984.1,5038.1
Exp/Cntr=0.3,0.1

Type RM Length L Ch R = 1,61808,1765,1765,1765
BEGIN DESCRIPTION:
Clear Fork Brazos Rv 16.0
END DESCRIPTION:
XS GIS Cut Line= 3
      1701354.97      7060088.01      1704355.00      7059588.00
      1704854.98      7059088.02
#Sta/Elev= 30
  1959.1 1456.61  2230.3 1440.08  2235.4 1435.66  2283.5 1432.39  2357.0 1416.58
  2473.6 1415.73  2526.9 1399.14  2557.3 1379.92  2656.1 1367.80  2739.8 1348.39
  2820.9 1355.12  3013.5 1352.83  3033.8 1345.58  3114.9 1332.60  3147.8 1319.61
  3269.5 1303.58  3507.7 1296.94  4359.3 1292.68  4868.7 1295.60  4946.1 1261.27
  4952.1 1260.27  5018.1 1261.27  5028.8 1269.35  5057.1 1277.28  5129.4 1272.03
  5212.6 1279.50  5297.5 1308.39  5362.1 1318.62  5429.1 1318.08  5707.6 1325.35
#Mann=6,-1,0
  1959.1    0.05       0  4946.1    0.07       0  5018.1    0.05       0
  5129.4    0.05       0  5362.1    0.12       0  5429.1    0.05       0
Bank Sta=4946.1,5018.1
Exp/Cntr=0.3,0.1

Type RM Length L Ch R = 1,60043,2827,2827,2827
BEGIN DESCRIPTION:
Mapping XS 6747de06
END DESCRIPTION:
XS GIS Cut Line= 3
      1701888.53      7060451.09      1703367.79      7061378.91
      1706536.44      7061107.57
#Sta/Elev= 30
  2012.3 1347.41  2057.4 1339.92  2188.2 1330.69  2696.0 1315.31  3277.0 1308.02
  3758.5 1310.65  3785.8 1315.19  3829.3 1309.60  4127.0 1310.49  4547.4 1290.78
  4859.7 1292.97  4889.8 1288.47  4909.9 1278.47  4950.0 1274.91  4970.1 1268.00
  4977.3 1260.64  4982.5 1259.64  5040.3 1260.64  5045.8 1263.11  5080.5 1278.13
  5145.4 1288.34  5170.8 1293.74  5245.1 1296.82  5416.5 1309.42  5522.1 1316.16
  5712.8 1309.37  6124.3 1321.29  6335.1 1320.79  6505.7 1314.22  6938.7 1322.80
#Mann=8,-1,0
  2012.3    0.05       0  4547.4    0.12       0  4977.3    0.07       0
  5040.3    0.12       0  5045.8    0.05       0  5145.4     0.1       0
  5245.1    0.12       0  5416.5    0.05       0
Bank Sta=4977.3,5040.3
Exp/Cntr=0.3,0.1

Type RM Length L Ch R = 1,57216,782,782,782
BEGIN DESCRIPTION:
Mapping XS b577ab63
END DESCRIPTION:
XS GIS Cut Line= 3
      1701906.01      7060529.85      1703420.31      7061553.97
      1703796.69      7064302.43
#Sta/Elev= 30
  1063.0 1336.41  1140.1 1331.22  1363.6 1322.88  1679.5 1314.61  2090.0 1307.94
  2356.7 1307.06  2818.1 1311.51  3477.0 1304.44  4096.3 1303.42  4530.3 1289.17
  4691.8 1293.41  4762.4 1287.47  4833.1 1287.90  4878.7 1278.04  4923.9 1276.21
  4944.1 1272.54  4955.9 1266.29  4964.3 1259.13  4971.6 1259.13  4976.8 1258.13
  5034.6 1259.13  5055.1 1271.21  5100.3 1282.92  5105.6 1287.43  5115.7 1290.59
  5186.3 1289.75  5236.8 1298.47  5327.7 1333.61  5529.5 1346.56  5665.2 1347.39
#Mann=3,-1,0
  1063.0    0.05       0  4971.6    0.03       0  5034.6    0.05       0
Bank Sta=4971.6,5034.6
Exp/Cntr=0.3,0.1

Type RM Length L Ch R = 1,56434,1682,1682,1682
BEGIN DESCRIPTION:
Mapping XS 5009936a
END DESCRIPTION:
XS GIS Cut Line= 4
      1701776.51      7061007.01      1702775.47      7061512.66
      1703046.79      7064324.44      1703564.77      7064472.44
#Sta/Elev= 30
  1495.5 1318.61  1538.6 1315.72  2083.4 1312.65  2491.3 1300.85  2710.9 1299.59
  2821.4 1304.04  2982.2 1304.53  3675.4 1297.06  4197.8 1297.40  4535.4 1288.06
  4623.3 1290.15  4680.0 1294.42  4780.5 1293.17  4820.7 1278.67  4853.3 1273.54
  4870.9 1270.69  4901.1 1276.19  4954.6 1265.65  4968.5 1259.07  4973.8 1258.07
  5031.5 1259.07  5031.7 1264.19  5056.9 1279.08  5112.0 1296.29  5142.2 1309.51
  5159.2 1320.56  5172.3 1323.60  5439.3 1327.14  5750.1 1340.93  5978.7 1344.64
#Mann=5,-1,0
  1495.5    0.05       0  4623.3    0.12       0  4853.3    0.05       0
  4968.5    0.07       0  5031.5    0.05       0
Bank Sta=4968.5,5031.5
Exp/Cntr=0.3,0.1

Type RM Length L Ch R = 1,54752,3473,3473,3473
BEGIN DESCRIPTION:
Mapping XS 6d3b0df2
END DESCRIPTION:
XS GIS Cut Line= 3
      1699770.27      7061090.06      1701748.47      7064284.93
      1703541.40      7064494.84
#Sta/Elev= 30
  1944.9 1467.94  1962.9 1467.45  2000.4 1465.17  2320.7 1373.45  2419.1 1350.49
  2659.9 1322.20  3291.1 1302.84  3596.0 1280.61  3617.3 1270.63  3742.0 1268.32
  3864.2 1281.28  3937.5 1272.19  4068.7 1288.92  4309.7 1291.50  4836.7 1293.21
  4894.7 1276.93  4946.7 1270.73  4960.4 1259.00  4969.4 1258.00  5068.4 1259.00
  5172.4 1282.96  5200.5 1274.45  5288.2 1290.49  5709.2 1307.63  6204.8 1313.71
  6542.9 1305.01  6766.4 1316.12  6867.1 1308.79  6974.4 1324.58  7507.8 1344.38
#Mann=8,-1,0
  1944.9    0.12       0  1962.9    0.05       0  2000.4    0.12       0
  2320.7    0.05       0  4309.7    0.12       0  4894.7    0.05       0
  4960.4    0.03       0  5068.4    0.05       0
#XS Ineff=2,0
    0.00 4141.30 1335.98 5858.70    0.00 1335.98
Permanent Ineff=
       F       F
Bank Sta=4960.4,5068.4
Exp/Cntr=0.3,0.1

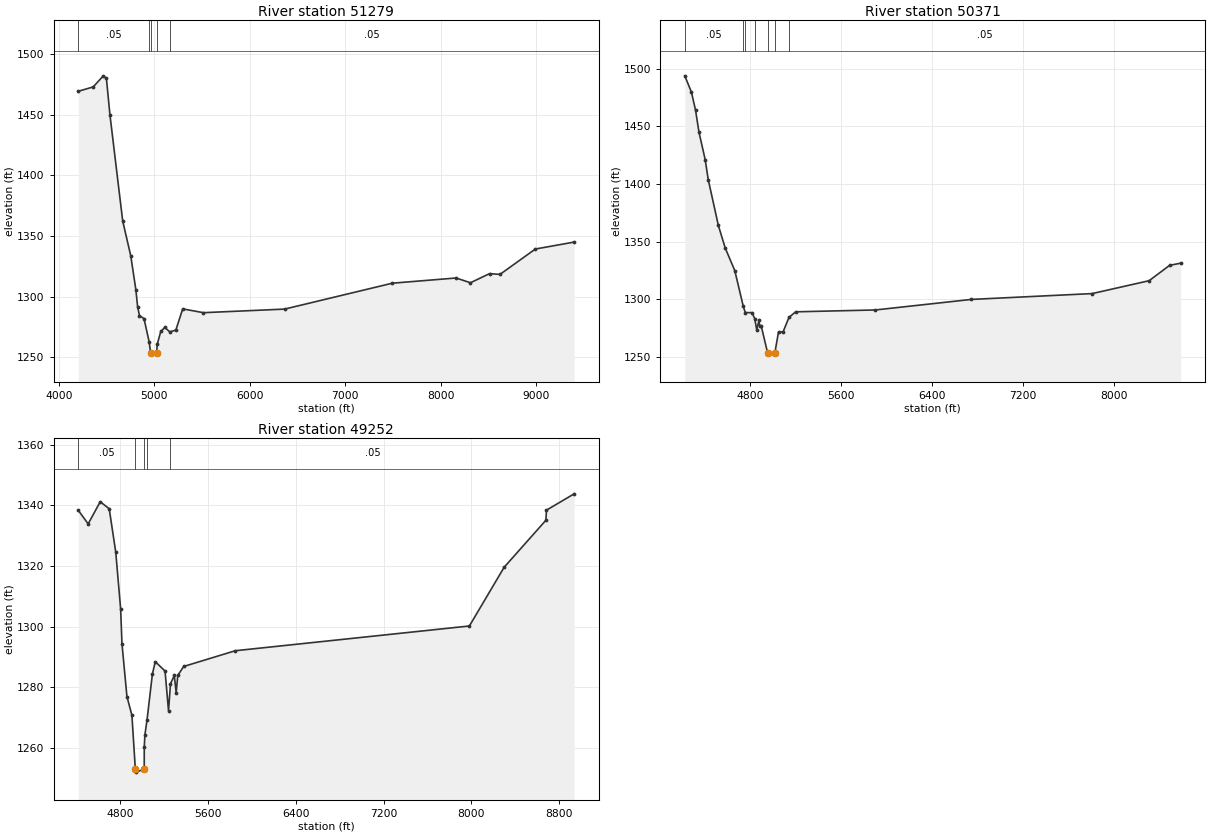
Type RM Length L Ch R = 1,51279,908,908,908
BEGIN DESCRIPTION:
Mapping XS 37890069
END DESCRIPTION:
XS GIS Cut Line= 4
      1698579.84      7063847.28      1701293.31      7064477.50
      1703560.36      7064547.53      1703700.25      7064565.01
#Sta/Elev= 30
  4203.4 1469.38  4359.4 1473.01  4465.3 1482.14  4497.6 1479.94  4535.1 1449.57
  4668.1 1362.42  4752.8 1333.56  4806.3 1305.59  4824.7 1291.47  4843.8 1284.35
  4891.6 1281.76  4945.6 1262.59  4960.7 1253.48  4966.0 1252.48  5023.7 1253.48
  5030.0 1260.60  5067.2 1271.18  5109.9 1274.55  5161.4 1270.83  5225.0 1272.31
  5296.9 1289.82  5514.1 1286.68  6364.6 1289.64  7493.6 1311.02  8161.3 1315.31
  8311.4 1311.36  8511.5 1318.90  8621.6 1318.30  8991.7 1339.21  9398.2 1344.95
#Mann=5,-1,0
  4203.4    0.05       0  4945.6    0.12       0  4960.7    0.07       0
  5023.7    0.12       0  5161.4    0.05       0
Bank Sta=4960.7,5023.7
Exp/Cntr=0.3,0.1

Type RM Length L Ch R = 1,50371,1119,1119,1119
BEGIN DESCRIPTION:
Mapping XS 911405e9
END DESCRIPTION:
XS GIS Cut Line= 3
      1698792.13      7065002.72      1699519.73      7064879.40
      1703131.57      7064682.17
#Sta/Elev= 30
  4226.8 1493.96  4285.2 1479.76  4321.0 1464.19  4351.4 1444.98  4405.9 1421.14
  4432.6 1403.83  4521.6 1363.97  4581.9 1344.34  4665.8 1324.78  4740.6 1293.66
  4758.0 1288.32  4818.0 1288.18  4841.5 1282.81  4858.6 1273.22  4878.6 1281.68
  4883.7 1277.05  4899.1 1276.22  4954.5 1253.18  4959.8 1252.18  5017.5 1253.18
  5050.2 1271.53  5090.2 1271.54  5141.6 1284.02  5200.4 1288.94  5901.4 1290.55
  6742.7 1299.70  7804.3 1304.77  8305.0 1315.96  8485.3 1329.30  8582.0 1331.20
#Mann=7,-1,0
  4226.8    0.05       0  4740.6    0.12       0  4758.0    0.05       0
  4841.5    0.12       0  4954.5    0.07       0  5017.5    0.12       0
  5141.6    0.05       0
Bank Sta=4954.5,5017.5
Exp/Cntr=0.3,0.1

Type RM Length L Ch R = 1,49252,0,0,0
BEGIN DESCRIPTION:
Mapping XS 646a58f9
END DESCRIPTION:
XS GIS Cut Line= 3
      1699393.91      7066166.84      1699919.08      7065886.75
      1703647.18      7064652.80
#Sta/Elev= 30
  4415.5 1338.37  4505.2 1333.92  4615.0 1341.21  4697.2 1338.92  4756.7 1324.61
  4801.3 1305.92  4813.4 1294.43  4858.7 1276.98  4904.1 1270.82  4935.4 1253.04
  4942.1 1252.04  5016.4 1253.04  5016.9 1260.26  5022.4 1264.27  5042.6 1269.39
  5091.1 1284.42  5117.5 1288.46  5206.5 1285.37  5238.1 1272.31  5256.0 1281.17
  5290.8 1283.92  5307.8 1278.24  5322.4 1283.95  5376.5 1286.89  5846.9 1292.08
  7982.2 1300.24  8299.3 1319.62  8679.9 1335.11  8685.2 1338.44  8937.7 1343.83
#Mann=5,-1,0
  4415.5    0.05       0  4935.4    0.03       0  5016.4    0.05       0
  5042.6    0.12       0  5256.0    0.05       0
Bank Sta=4935.4,5016.4
Exp/Cntr=0.3,0.1

Chan Stop Cuts=-1