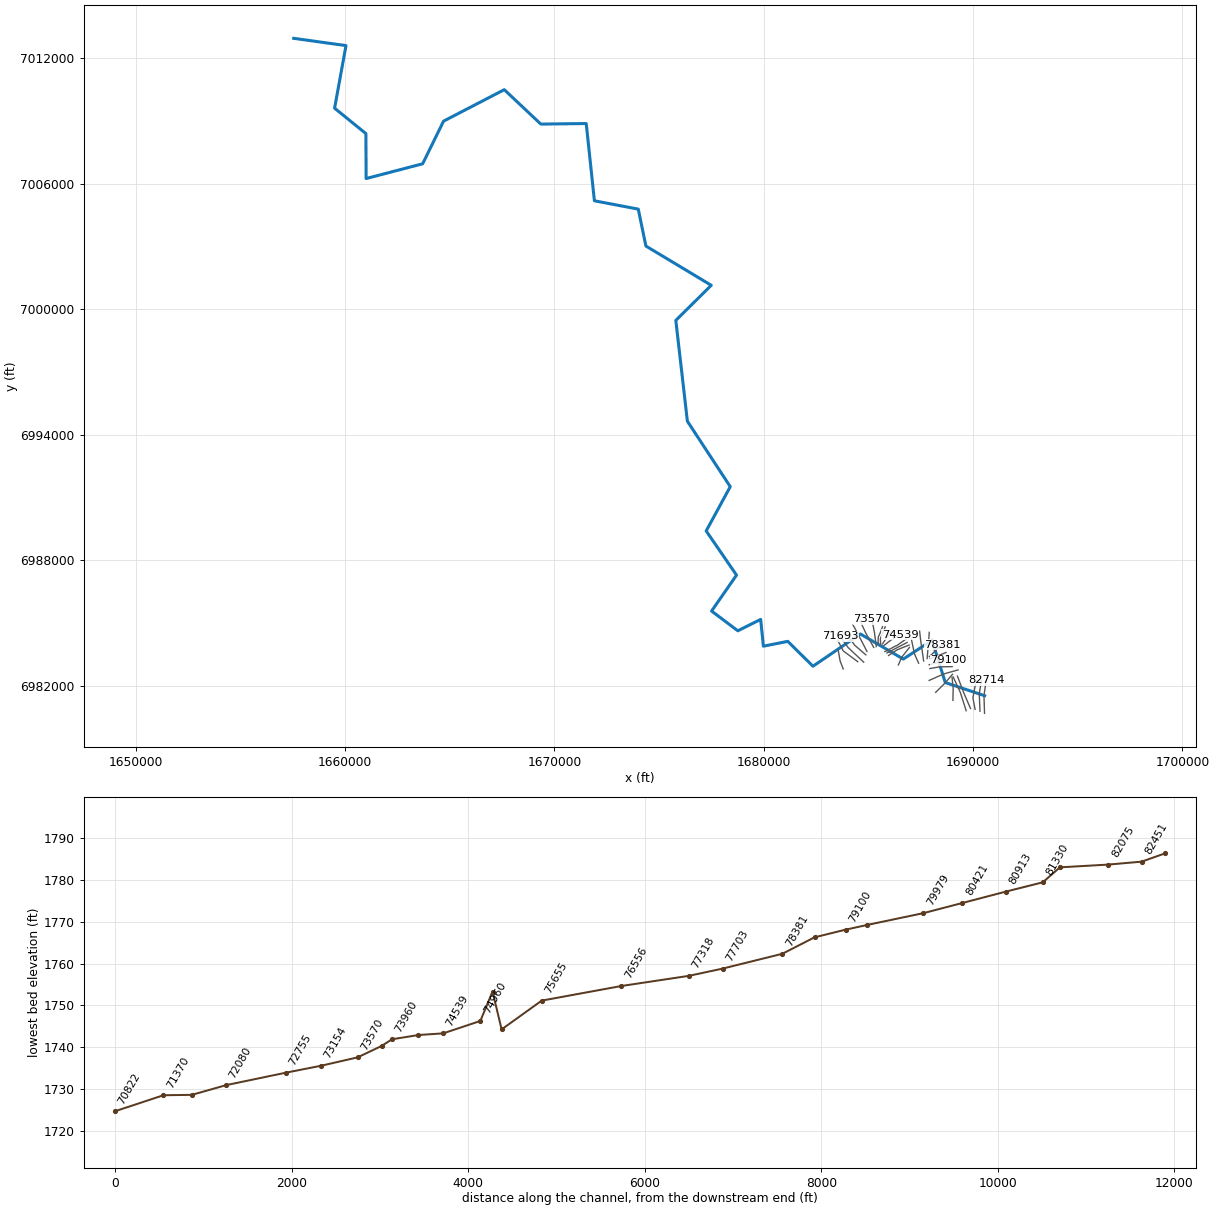
--- Fish Creek.prj (project) ---

Proj Title=Fish Creek Base Level Engineering
Current Plan=p01
Default Exp/Contr=0.3,0.1
English Units
Geom File=g01
Flow File=f01
Plan File=p01
Y Axis Title=Elevation
X Axis Title(PF)=Main Channel Distance
X Axis Title(XS)=Station
BEGIN DESCRIPTION:
Fish Creek
END DESCRIPTION:
DSS Export Rating Curves= 0
DSS Export Rating Curve Sorted= 0
DSS Export Volume Flow Curves= 0
DXF OffsetX= 0
DXF OffsetY= 0
DXF ScaleX= 1
DXF ScaleY= 10

--- Fish Creek.p01 (plan) ---

Plan Title=Multiple Run
Short Identifier=Multiple
Geom File=g01
Flow File=f01
Subcritical Flow
K Sum by GR= 0
Std Step Tol= 0.01
Critical Tol= 0.01
Num of Std Step Trials= 20
Max Error Tol= 0.3
Flow Tol Ratio= 0.001
Split Flow NTrial= 30
Split Flow Tol= 0.02
Split Flow Ratio= 0.02
Log Output Level= 0
Friction Slope Method= 1
Unsteady Friction Slope Method= 2
Unsteady Bridges Friction Slope Method= 1
Parabolic Critical Depth
Global Vel Dist=  1 , 1 , 1
Global Log Level= 0
CheckData=True
Encroach Param= -1, 0, 0, 0
BEGIN DESCRIPTION:
Multiple Run
END DESCRIPTION:

--- Fish Creek.f01 (steady flow) ---

Flow Title=Multiple
Number of Profiles=7
Profile Names=10-year,25-year,50-year,1pct_min,100-year,1pct_plu,500-year
River Rch & RM= Fish Creek,Reach-1,82714
     246     338     413     252     503    1004     754
River Rch & RM= Fish Creek,Reach-1,80913
     315     438     539     330     659    1315     998
River Rch & RM= Fish Creek,Reach-1,73154
     402     564     700     432     861    1718    1322
River Rch & RM= Fish Creek,Reach-1,69294
     503     714     892     554    1106    2207    1722
River Rch & RM= Fish Creek,Reach-1,66699
     541     770     964     599    1196    2386    1864
River Rch & RM= Fish Creek,Reach-1,62029
     938    1367    1739    1098    2191    4371    3520
River Rch & RM= Fish Creek,Reach-1,55530
    1026    1499    1911    1208    2409    4807    3881
River Rch & RM= Fish Creek,Reach-1,50917
    1379    2036    2613    1662    3315    6615    5406
River Rch & RM= Fish Creek,Reach-1,44957
    1447    2137    2744    1745    3483    6949    5682
River Rch & RM= Fish Creek,Reach-1,38784
    1789    2659    3428    2188    4365    8710    7172
River Rch & RM= Fish Creek,Reach-1,32277
    1897    2823    3644    2329    4646    9270    7649
River Rch & RM= Fish Creek,Reach-1,25489
    1995    2973    3840    2455    4899    9775    8075
River Rch & RM= Fish Creek,Reach-1,17925
    1949    2915    3773    2417    4823    9623    7985
River Rch & RM= Fish Creek,Reach-1,14617
    1994    2985    3867    2479    4946    9868    8199
River Rch & RM= Fish Creek,Reach-1,12454
    2166    3250    4216    2707    5401   10776    8979
River Rch & RM= Fish Creek,Reach-1,5587
    2205    3310    4296    2759    5506   10985    9161
Boundary for River Rch & Prof#=Fish Creek,Reach-1,1
Up Type=0
Dn Type=3
Dn Slope=0.005
Boundary for River Rch & Prof#=Fish Creek,Reach-1,2
Up Type=0
Dn Type=3
Dn Slope=0.005
Boundary for River Rch & Prof#=Fish Creek,Reach-1,3
Up Type=0
Dn Type=3
Dn Slope=0.005
Boundary for River Rch & Prof#=Fish Creek,Reach-1,4
Up Type=0
Dn Type=3
Dn Slope=0.005
Boundary for River Rch & Prof#=Fish Creek,Reach-1,5
Up Type=0
Dn Type=3
Dn Slope=0.005
Boundary for River Rch & Prof#=Fish Creek,Reach-1,6
Up Type=0
Dn Type=3
Dn Slope=0.005
Boundary for River Rch & Prof#=Fish Creek,Reach-1,7
Up Type=0
Dn Type=3
Dn Slope=0.005

--- Fish Creek.g01 (geometry) ---

Geom Title=Existing Conditions

River Reach=Fish Creek,Reach-1
Reach XY= 30
      1690555.00      6981538.00      1688674.44      6982167.45
      1688043.05      6984186.08      1686670.36      6983287.89
      1684619.83      6984486.81      1682355.00      6982945.55
      1681153.42      6984134.18      1679988.20      6983904.41
      1679857.31      6985182.18      1678765.66      6984638.33
      1677512.74      6985581.86      1678704.07      6987298.48
      1677254.74      6989407.94      1678404.50      6991522.76
      1676356.62      6994649.83      1675804.52      6999465.24
      1677497.21      7001141.42      1674374.77      7003017.87
      1674011.17      7004780.14      1671915.52      7005178.21
      1671525.20      7008868.41      1669356.47      7008841.54
      1667610.94      7010485.74      1664710.61      7008982.41
      1663711.17      7006945.86      1661010.86      7006240.07
      1661001.25      7008386.45      1659505.55      7009601.97
      1660049.55      7012591.01      1657555.00      7012938.00

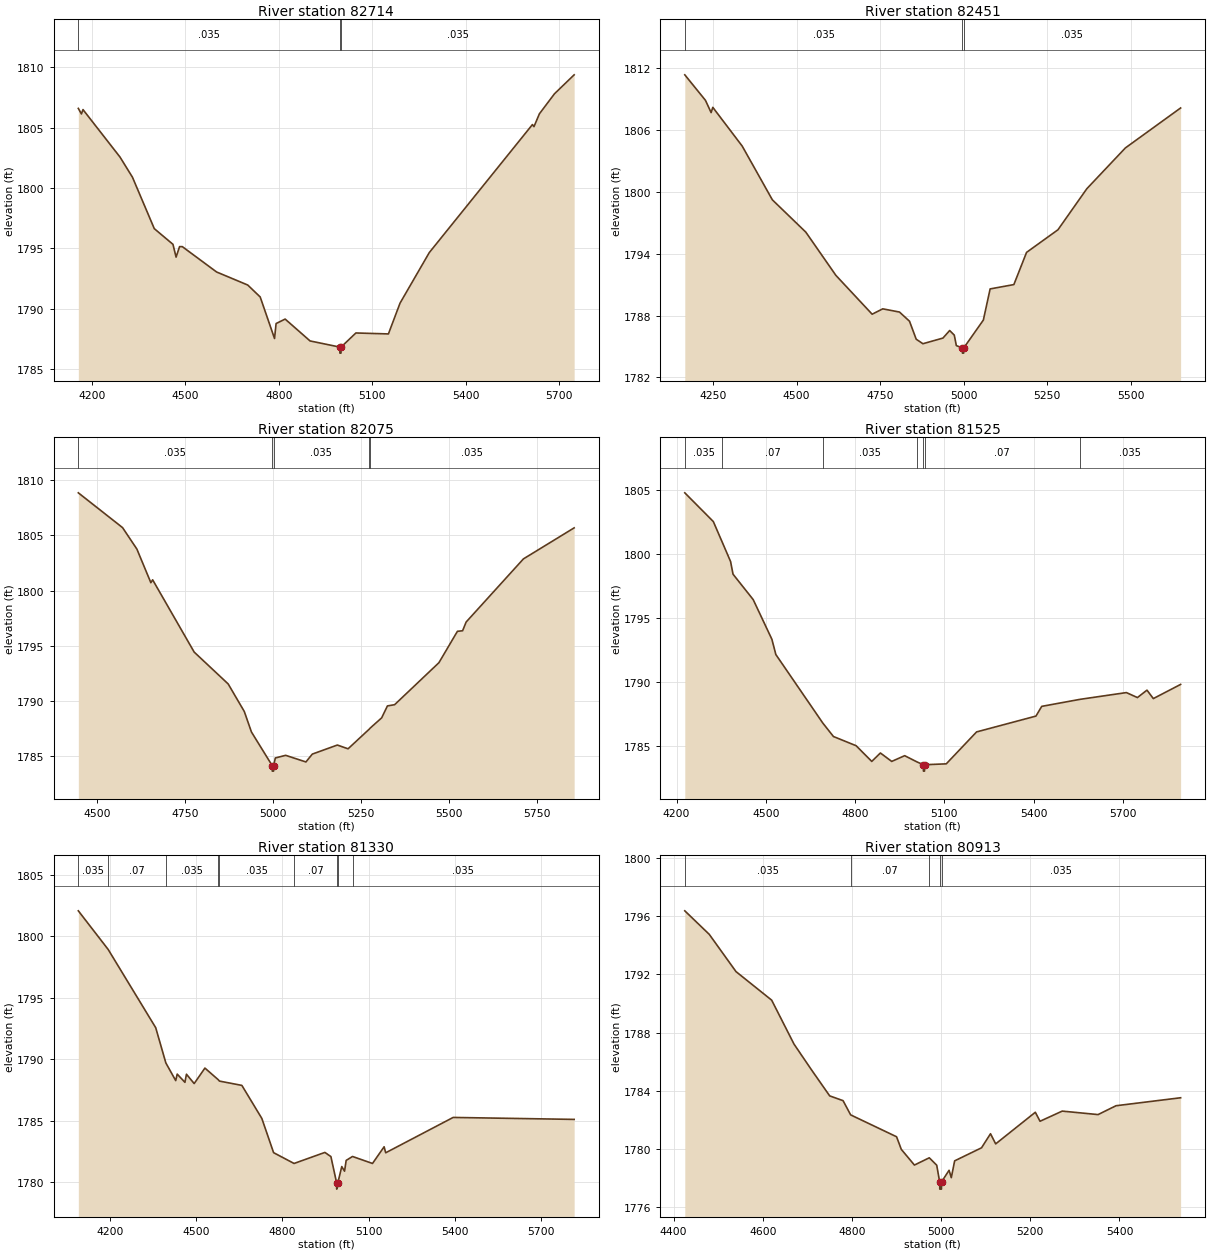
Type RM Length L Ch R = 1,82714,263,263,263
BEGIN DESCRIPTION:
Fish Creek 138.0
END DESCRIPTION:
XS GIS Cut Line= 3
      1690550.36      6980694.27      1690523.12      6981537.93
      1690628.49      6982278.48
#Sta/Elev= 30
  4155.9 1806.60  4165.9 1806.14  4170.9 1806.50  4289.7 1802.57  4329.7 1800.90
  4399.8 1796.64  4459.8 1795.34  4469.8 1794.28  4480.9 1795.15  4489.8 1795.15
  4599.9 1793.05  4699.9 1791.97  4739.9 1790.98  4785.9 1787.54  4790.9 1788.78
  4820.0 1789.15  4900.0 1787.34  4995.5 1786.83  4995.8 1786.33  4999.3 1786.33
  4999.5 1786.83  5047.2 1788.00  5151.6 1787.92  5188.9 1790.47  5282.9 1794.66
  5614.0 1805.26  5619.0 1805.09  5636.4 1806.15  5684.8 1807.81  5748.0 1809.38
#Mann=3,-1,0
  4155.9   0.035       0  4995.5   0.035       0  4999.5   0.035       0
Bank Sta=4995.5,4999.5
Exp/Cntr=0.3,0.1

Type RM Length L Ch R = 1,82451,376,376,376
BEGIN DESCRIPTION:
Mapping XS 5b446864
END DESCRIPTION:
XS GIS Cut Line= 3
      1690333.35      6980796.26      1690298.62      6981633.93
      1690407.13      6982269.75
#Sta/Elev= 30
  4165.7 1811.32  4227.5 1808.85  4244.5 1807.66  4249.5 1808.17  4337.6 1804.41
  4427.7 1799.21  4527.8 1796.08  4617.8 1791.89  4726.2 1788.13  4757.9 1788.65
  4808.0 1788.34  4838.0 1787.45  4858.0 1785.71  4878.1 1785.27  4938.1 1785.82
  4958.1 1786.55  4972.0 1786.10  4978.1 1785.09  4996.2 1784.86  4996.4 1784.36
  4999.9 1784.36  5000.2 1784.86  5058.9 1787.56  5079.2 1790.58  5150.2 1791.00
  5188.2 1794.12  5282.1 1796.31  5368.6 1800.29  5483.9 1804.24  5649.1 1808.11
#Mann=3,-1,0
  4165.7   0.035       0  4996.2   0.035       0  5000.2   0.035       0
Bank Sta=4996.2,5000.2
Exp/Cntr=0.3,0.1

Type RM Length L Ch R = 1,82075,550,550,550
BEGIN DESCRIPTION:
Mapping XS 33435087
END DESCRIPTION:
XS GIS Cut Line= 3
      1690098.97      6980884.36      1689994.81      6981436.44
      1690151.06      6982269.79
#Sta/Elev= 30
  4446.0 1808.84  4571.8 1805.69  4612.5 1803.75  4652.2 1800.71  4657.3 1800.97
  4775.4 1794.43  4872.0 1791.55  4917.8 1789.06  4938.2 1787.20  4997.2 1784.16
  4997.5 1783.66  5001.0 1783.66  5001.2 1784.16  5006.1 1784.85  5035.4 1785.09
  5093.1 1784.49  5111.2 1785.20  5182.4 1786.02  5212.9 1785.68  5272.5 1787.44
  5276.0 1787.56  5308.4 1788.48  5324.8 1789.56  5345.2 1789.67  5471.2 1793.47
  5523.8 1796.31  5538.5 1796.36  5548.6 1797.15  5711.4 1802.86  5855.7 1805.67
#Mann=5,-1,0
  4446.0   0.035       0  4997.2   0.035       0  5001.2   0.035       0
  5272.5    0.07       0  5276.0   0.035       0
Bank Sta=4997.2,5001.2
Exp/Cntr=0.3,0.1

Type RM Length L Ch R = 1,81525,195,195,195
BEGIN DESCRIPTION:
Mapping XS 6b03084e
END DESCRIPTION:
XS GIS Cut Line= 3
      1689879.65      6980929.04      1689573.65      6981640.87
      1689254.86      6982473.63
#Sta/Elev= 30
  4227.7 1804.79  4323.6 1802.54  4353.3 1800.94  4381.6 1799.41  4389.8 1798.42
  4457.6 1796.43  4520.5 1793.32  4533.7 1792.13  4691.7 1786.76  4727.3 1785.71
  4803.5 1784.99  4856.1 1783.76  4885.1 1784.42  4923.2 1783.76  4966.7 1784.21
  5008.2 1783.72  5029.6 1783.50  5029.8 1783.00  5033.3 1783.00  5033.6 1783.50
  5106.5 1783.57  5208.4 1786.07  5408.0 1787.31  5427.3 1788.07  5555.9 1788.62
  5711.8 1789.15  5749.0 1788.76  5781.1 1789.34  5802.5 1788.68  5894.2 1789.79
#Mann=7,-1,0
  4227.7   0.035       0  4353.3    0.07       0  4691.7   0.035       0
  5008.2    0.07       0  5029.6   0.035       0  5033.6    0.07       0
  5555.9   0.035       0
Bank Sta=5029.6,5033.6
Exp/Cntr=0.3,0.1

Type RM Length L Ch R = 1,81330,417,417,417
BEGIN DESCRIPTION:
Mapping XS 6be0d98f
END DESCRIPTION:
XS GIS Cut Line= 3
      1689673.47      6980820.60      1689393.53      6981695.12
      1689054.99      6982428.63
#Sta/Elev= 30
  4089.7 1802.08  4193.4 1798.94  4359.1 1792.56  4394.4 1789.69  4428.7 1788.25
  4433.9 1788.78  4460.8 1788.11  4466.1 1788.77  4493.0 1788.01  4530.4 1789.27
  4576.9 1788.32  4581.1 1788.21  4659.0 1787.86  4728.5 1785.17  4769.5 1782.38
  4840.7 1781.50  4948.0 1782.40  4969.0 1782.06  4989.0 1779.91  4989.2 1779.41
  4993.0 1779.91  5006.8 1781.25  5016.5 1780.87  5022.1 1781.75  5044.2 1782.07
  5113.8 1781.50  5154.2 1782.86  5159.7 1782.37  5394.6 1785.25  5815.8 1785.09
#Mann=9,-1,0
  4089.7   0.035       0  4193.4    0.07       0  4394.4   0.035       0
  4576.9    0.07       0  4581.1   0.035       0  4840.7    0.07       0
  4989.0    0.07       0  4993.0    0.07       0  5044.2   0.035       0
Bank Sta=4989,4993
Exp/Cntr=0.3,0.1

Type RM Length L Ch R = 1,80913,492,492,492
BEGIN DESCRIPTION:
Mapping XS 534bdb97
END DESCRIPTION:
XS GIS Cut Line= 3
      1689040.96      6981313.19      1689051.81      6981890.44
      1688997.55      6982422.13
#Sta/Elev= 30
  4425.3 1796.39  4480.1 1794.77  4540.1 1792.20  4620.1 1790.23  4670.2 1787.20
  4710.2 1785.39  4750.2 1783.63  4780.2 1783.30  4797.2 1782.32  4900.2 1780.81
  4910.8 1779.94  4940.2 1778.86  4973.5 1779.36  4990.2 1778.85  4996.8 1777.70
  4997.1 1777.20  5000.7 1777.20  5001.0 1777.70  5017.9 1778.50  5022.9 1777.99
  5030.4 1779.15  5090.7 1780.05  5110.8 1781.02  5122.4 1780.32  5211.3 1782.50
  5221.9 1781.88  5271.6 1782.58  5352.0 1782.34  5392.2 1782.95  5537.1 1783.50
#Mann=5,-1,0
  4425.3   0.035       0  4797.2    0.07       0  4973.5   0.035       0
  4996.8   0.035       0  5001.0   0.035       0
Bank Sta=4996.8,5001
Exp/Cntr=0.3,0.1

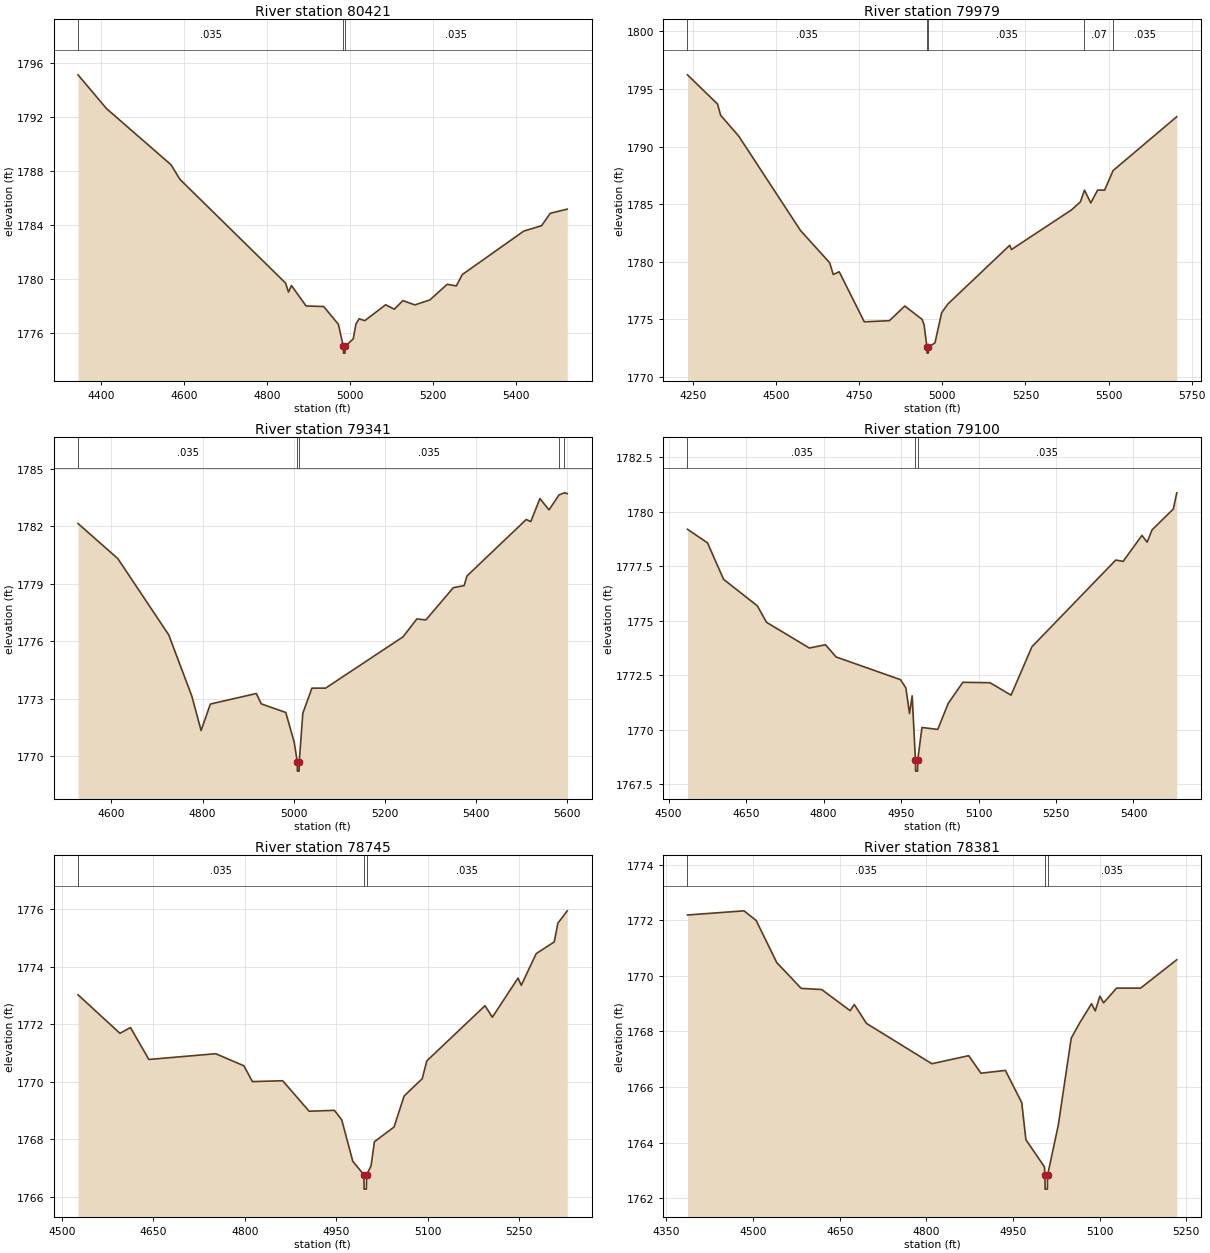
Type RM Length L Ch R = 1,80421,442,442,442
BEGIN DESCRIPTION:
Mapping XS 0cb33d40
END DESCRIPTION:
XS GIS Cut Line= 3
      1688216.27      6981699.43      1688680.71      6982159.53
      1689019.24      6982560.99
#Sta/Elev= 30
  4345.1 1795.14  4413.9 1792.63  4569.4 1788.46  4590.7 1787.38  4845.3 1779.68
  4852.3 1779.01  4859.4 1779.50  4894.7 1777.98  4937.1 1777.94  4972.5 1776.62
  4984.5 1774.98  4984.8 1774.48  4988.5 1774.48  4988.8 1774.98  5008.3 1775.54
  5014.9 1776.65  5022.6 1777.03  5036.1 1776.89  5086.4 1778.07  5107.2 1777.74
  5128.0 1778.38  5156.6 1778.06  5193.0 1778.43  5234.6 1779.59  5256.7 1779.47
  5271.0 1780.31  5419.3 1783.54  5462.2 1783.94  5483.0 1784.86  5524.0 1785.17
#Mann=3,-1,0
  4345.1   0.035       0  4984.5   0.035       0  4988.8   0.035       0
Bank Sta=4984.5,4988.8
Exp/Cntr=0.3,0.1

Type RM Length L Ch R = 1,79979,638,638,638
BEGIN DESCRIPTION:
Mapping XS b6b974b0
END DESCRIPTION:
XS GIS Cut Line= 3
      1687903.83      6982268.05      1688606.93      6982578.37
      1689283.98      6982769.33
#Sta/Elev= 30
  4233.2 1796.23  4323.6 1793.69  4332.9 1792.72  4387.5 1790.90  4573.3 1782.70
  4660.8 1779.91  4671.8 1778.88  4689.7 1779.12  4765.1 1774.77  4840.5 1774.87
  4887.1 1776.14  4939.2 1774.98  4945.0 1774.51  4953.8 1772.55  4954.1 1772.05
  4957.8 1772.05  4958.1 1772.55  4977.8 1772.95  4997.9 1775.56  5017.0 1776.33
  5202.7 1781.42  5207.8 1781.05  5388.3 1784.49  5415.3 1785.19  5427.6 1786.21
  5446.5 1785.10  5467.3 1786.22  5488.1 1786.21  5513.6 1787.91  5705.2 1792.59
#Mann=5,-1,0
  4233.2   0.035       0  4953.8   0.035       0  4958.1   0.035       0
  5427.6    0.07       0  5513.6   0.035       0
Bank Sta=4953.8,4958.1
Exp/Cntr=0.3,0.1

Type RM Length L Ch R = 1,79341,241,241,241
BEGIN DESCRIPTION:
Mapping XS ae890af1
END DESCRIPTION:
XS GIS Cut Line= 3
      1687939.01      6982834.94      1688406.00      6982916.54
      1689004.95      6982926.95
#Sta/Elev= 30
  4526.6 1782.14  4613.9 1780.31  4725.6 1776.33  4776.3 1773.13  4796.6 1771.34
  4816.9 1772.72  4917.7 1773.27  4928.6 1772.73  4982.3 1772.28  5000.7 1770.74
  5007.5 1769.72  5007.8 1769.22  5011.6 1769.22  5011.9 1769.72  5019.7 1772.24
  5039.7 1773.55  5069.7 1773.55  5239.7 1776.23  5269.7 1777.16  5289.7 1777.11
  5349.7 1778.79  5373.5 1778.90  5379.7 1779.40  5509.7 1782.35  5519.7 1782.24
  5539.7 1783.44  5559.7 1782.85  5581.6 1783.63  5593.4 1783.74  5599.7 1783.70
#Mann=5,-1,0
  4526.6   0.035       0  5007.5   0.035       0  5011.9   0.035       0
  5581.6    0.07       0  5593.4   0.035       0
Bank Sta=5007.5,5011.9
Exp/Cntr=0.3,0.1

Type RM Length L Ch R = 1,79100,355,355,355
BEGIN DESCRIPTION:
Mapping XS a3708792
END DESCRIPTION:
XS GIS Cut Line= 3
      1687907.72      6983017.23      1688350.45      6983140.50
      1688831.54      6983220.10
#Sta/Elev= 30
  4536.6 1779.19  4575.3 1778.57  4606.4 1776.90  4671.9 1775.68  4689.5 1774.93
  4772.5 1773.75  4803.7 1773.90  4824.4 1773.34  4949.0 1772.30  4959.4 1771.92
  4966.4 1770.75  4971.6 1771.56  4977.9 1768.61  4978.2 1768.11  4982.0 1768.11
  4982.3 1768.61  4990.5 1770.11  5021.1 1770.02  5041.3 1771.21  5069.7 1772.18
  5122.4 1772.16  5163.0 1771.59  5203.5 1773.81  5365.7 1777.78  5380.0 1777.72
  5416.4 1778.91  5426.5 1778.60  5435.9 1779.16  5477.2 1780.12  5483.8 1780.86
#Mann=3,-1,0
  4536.6   0.035       0  4977.9   0.035       0  4982.3   0.035       0
Bank Sta=4977.9,4982.3
Exp/Cntr=0.3,0.1

Type RM Length L Ch R = 1,78745,364,364,364
BEGIN DESCRIPTION:
Mapping XS 69426c67
END DESCRIPTION:
XS GIS Cut Line= 3
      1687960.69      6983311.95      1688402.05      6983479.90
      1688709.32      6983600.99
#Sta/Elev= 30
  4526.6 1773.02  4595.4 1771.68  4612.7 1771.88  4642.8 1770.77  4752.5 1770.97
  4798.7 1770.55  4812.7 1770.00  4862.3 1770.03  4905.7 1768.97  4947.2 1769.00
  4959.2 1768.67  4977.3 1767.23  4995.5 1766.76  4995.8 1766.26  4999.6 1766.26
  5000.0 1766.76  5007.3 1767.07  5012.8 1767.91  5045.0 1768.42  5061.5 1769.50
  5091.2 1770.10  5098.7 1770.72  5194.2 1772.64  5206.2 1772.24  5248.3 1773.60
  5253.7 1773.35  5278.1 1774.45  5307.8 1774.86  5313.7 1775.51  5329.1 1775.94
#Mann=3,-1,0
  4526.6   0.035       0  4995.5   0.035       0  5000.0   0.035       0
Bank Sta=4995.5,5000
Exp/Cntr=0.3,0.1

Type RM Length L Ch R = 1,78381,678,678,678
BEGIN DESCRIPTION:
Mapping XS 7329c623
END DESCRIPTION:
XS GIS Cut Line= 3
      1687912.61      6983402.05      1688355.18      6983830.17
      1688536.39      6983973.99
#Sta/Elev= 30
  4386.5 1772.19  4484.4 1772.34  4505.5 1771.99  4541.0 1770.48  4583.4 1769.55
  4618.7 1769.51  4668.1 1768.75  4675.3 1768.97  4696.4 1768.29  4809.6 1766.84
  4873.4 1767.13  4894.5 1766.50  4936.9 1766.60  4965.2 1765.44  4972.4 1764.11
  5004.5 1763.13  5005.4 1762.83  5005.7 1762.33  5009.6 1762.33  5009.9 1762.83
  5028.4 1764.62  5050.9 1767.76  5065.3 1768.30  5086.1 1769.00  5092.5 1768.74
  5100.5 1769.27  5106.9 1769.03  5129.4 1769.56  5171.0 1769.56  5233.6 1770.58
#Mann=3,-1,0
  4386.5   0.035       0  5005.4   0.035       0  5009.9   0.035       0
Bank Sta=5005.4,5009.9
Exp/Cntr=0.3,0.1

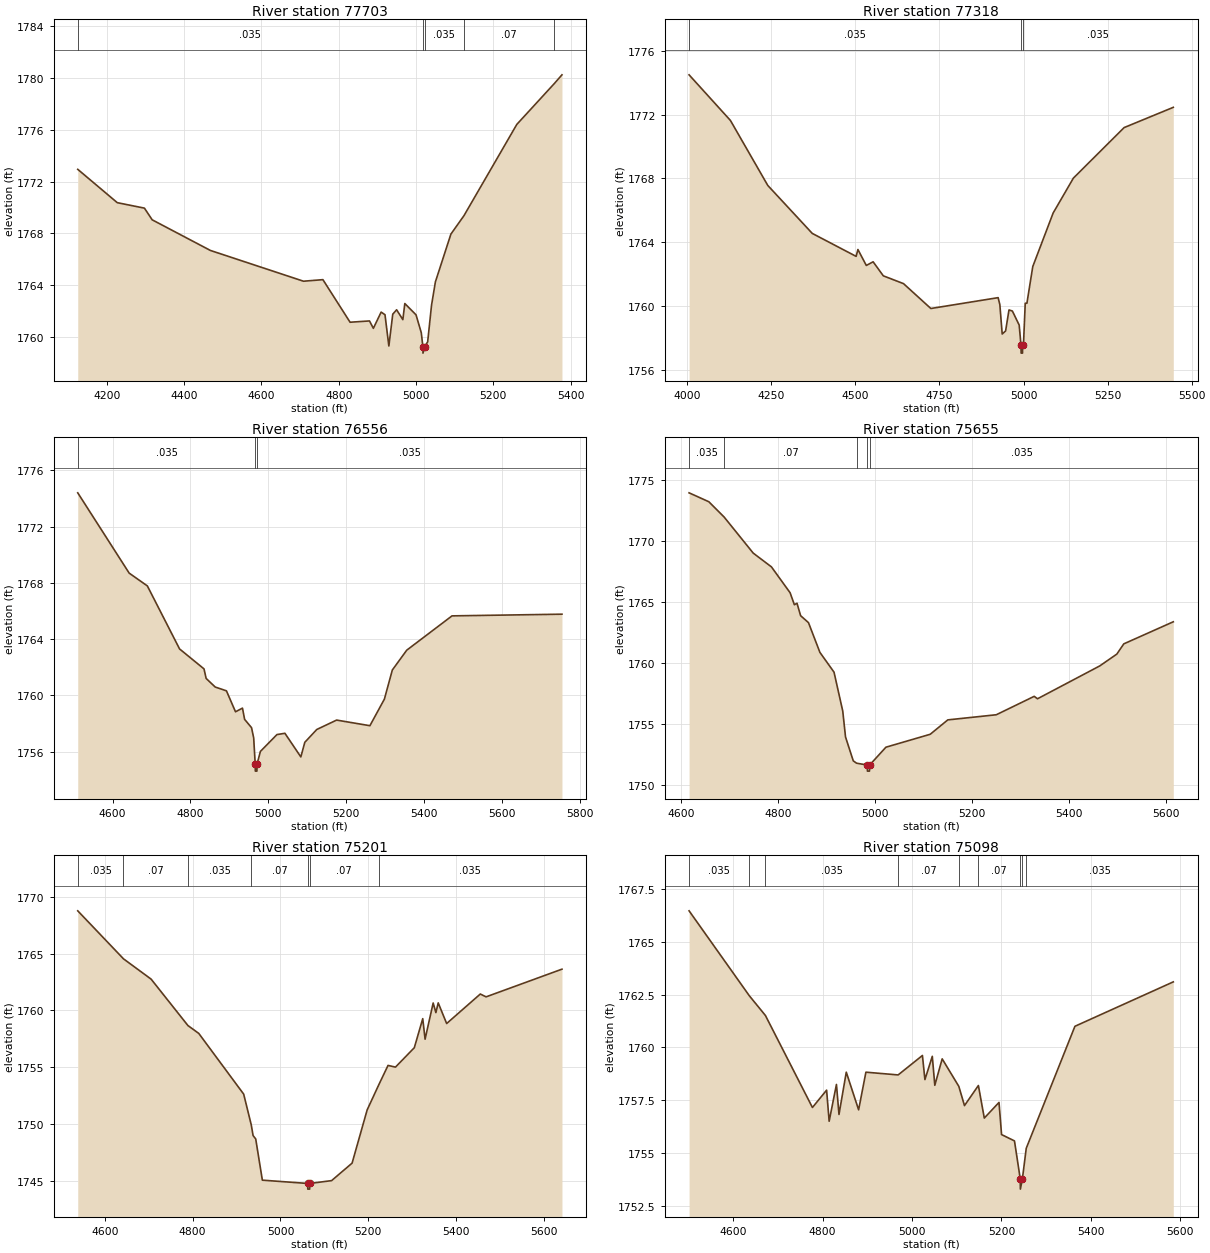
Type RM Length L Ch R = 1,77703,385,385,385
BEGIN DESCRIPTION:
Mapping XS c0c01369
END DESCRIPTION:
XS GIS Cut Line= 3
      1687808.43      6983316.08      1687883.95      6984201.52
      1687909.88      6984564.54
#Sta/Elev= 30
  4124.9 1772.94  4227.2 1770.37  4297.4 1769.95  4317.5 1769.05  4468.1 1766.69
  4708.9 1764.32  4759.1 1764.44  4829.4 1761.16  4879.6 1761.26  4889.6 1760.69
  4909.7 1761.94  4919.7 1761.74  4929.7 1759.33  4939.8 1761.78  4949.8 1762.12
  4965.9 1761.36  4971.0 1762.60  5000.0 1761.73  5013.6 1760.35  5017.7 1759.28
  5018.0 1758.78  5022.4 1759.28  5030.1 1759.65  5040.1 1762.47  5050.1 1764.27
  5090.2 1767.95  5124.0 1769.37  5260.7 1776.40  5357.5 1779.54  5377.5 1780.22
#Mann=5,-1,0
  4124.9   0.035       0  5017.7   0.035       0  5022.4   0.035       0
  5124.0    0.07       0  5357.5   0.035       0
Bank Sta=5017.7,5022.4
Exp/Cntr=0.3,0.1

Type RM Length L Ch R = 1,77318,762,762,762
BEGIN DESCRIPTION:
Mapping XS 90e55838
END DESCRIPTION:
XS GIS Cut Line= 3
      1687641.76      6983196.33      1687498.54      6984188.50
      1687449.08      6984623.24
#Sta/Elev= 30
  4005.4 1774.50  4128.3 1771.64  4239.5 1767.56  4371.8 1764.55  4502.2 1763.11
  4507.5 1763.54  4532.5 1762.54  4552.7 1762.77  4583.0 1761.89  4643.1 1761.40
  4724.4 1759.84  4924.5 1760.52  4929.6 1760.08  4936.6 1758.24  4946.7 1758.43
  4956.8 1759.75  4966.9 1759.68  4987.1 1758.80  4992.5 1757.54  4992.9 1757.04
  4997.0 1757.04  4997.3 1757.54  5000.0 1757.65  5005.1 1760.17  5010.1 1760.17
  5027.5 1762.47  5088.1 1765.83  5148.3 1768.02  5299.2 1771.19  5445.4 1772.46
#Mann=3,-1,0
  4005.4   0.035       0  4992.5   0.035       0  4997.3   0.035       0
Bank Sta=4992.5,4997.3
Exp/Cntr=0.3,0.1

Type RM Length L Ch R = 1,76556,901,901,901
BEGIN DESCRIPTION:
Mapping XS 26f08538
END DESCRIPTION:
XS GIS Cut Line= 3
      1687401.75      6983088.67      1687202.10      6983542.23
      1687048.30      6984274.40
#Sta/Elev= 30
  4510.5 1774.41  4642.6 1768.70  4689.3 1767.79  4772.0 1763.31  4834.8 1761.89
  4840.3 1761.21  4863.6 1760.60  4892.4 1760.33  4915.7 1758.84  4933.6 1759.10
  4939.1 1758.30  4956.9 1757.71  4962.4 1756.98  4966.3 1755.12  4966.6 1754.62
  4970.7 1754.62  4971.1 1755.12  4979.6 1756.02  5022.2 1757.22  5042.6 1757.31
  5083.5 1755.63  5093.7 1756.67  5124.4 1757.58  5175.4 1758.25  5260.9 1757.85
  5298.1 1759.74  5318.5 1761.81  5355.5 1763.22  5471.8 1765.66  5754.2 1765.78
#Mann=3,-1,0
  4510.5   0.035       0  4966.3   0.035       0  4971.1   0.035       0
Bank Sta=4966.3,4971.1
Exp/Cntr=0.3,0.1

Type RM Length L Ch R = 1,75655,454,454,454
BEGIN DESCRIPTION:
Mapping XS 6994e740
END DESCRIPTION:
XS GIS Cut Line= 3
      1686433.86      6983006.18      1686585.78      6983364.28
      1686963.01      6983843.40
#Sta/Elev= 30
  4616.5 1773.94  4657.2 1773.21  4688.9 1771.95  4748.8 1769.00  4786.4 1767.87
  4824.9 1765.75  4833.7 1764.77  4839.1 1764.89  4846.6 1763.87  4862.8 1763.30
  4886.4 1760.86  4915.5 1759.24  4933.5 1756.05  4939.2 1753.93  4955.2 1751.97
  4962.1 1751.78  4984.1 1751.63  4984.4 1751.13  4988.6 1751.13  4989.0 1751.63
  5022.5 1753.09  5113.9 1754.15  5150.2 1755.33  5250.2 1755.75  5328.4 1757.26
  5335.2 1757.06  5463.5 1759.75  5498.8 1760.72  5513.2 1761.56  5615.3 1763.37
#Mann=5,-1,0
  4616.5   0.035       0  4688.9    0.07       0  4962.1   0.035       0
  4984.1   0.035       0  4989.0   0.035       0
Bank Sta=4984.1,4989
Exp/Cntr=0.3,0.1

Type RM Length L Ch R = 1,75201,103,103,103
BEGIN DESCRIPTION:
Mapping XS 0e7c022d
END DESCRIPTION:
XS GIS Cut Line= 4
      1685969.46      6983461.94      1686355.74      6983715.84
      1686557.57      6983804.82      1686948.15      6983956.71
#Sta/Elev= 30
  4538.7 1768.77  4642.8 1764.54  4705.7 1762.75  4789.5 1758.66  4814.1 1757.97
  4916.3 1752.62  4933.5 1749.92  4937.7 1748.97  4943.7 1748.67  4958.8 1745.04
  5061.8 1744.75  5062.2 1744.25  5066.4 1744.25  5066.8 1744.75  5116.4 1745.00
  5163.0 1746.54  5197.3 1751.23  5223.6 1753.43  5244.8 1755.15  5261.7 1755.00
  5304.6 1756.71  5323.8 1759.27  5329.1 1757.46  5347.5 1760.65  5353.7 1759.80
  5359.0 1760.66  5378.2 1758.84  5454.8 1761.44  5467.9 1761.19  5640.6 1763.63
#Mann=7,-1,0
  4538.7   0.035       0  4642.8    0.07       0  4789.5   0.035       0
  4933.5    0.07       0  5061.8    0.07       0  5066.8    0.07       0
  5223.6   0.035       0
Bank Sta=5061.8,5066.8
Exp/Cntr=0.3,0.1

Type RM Length L Ch R = 1,75098,138,138,138
BEGIN DESCRIPTION:
Mapping XS cc9791cc
END DESCRIPTION:
XS GIS Cut Line= 3
      1685891.37      6983576.97      1686336.21      6983813.50
      1686850.29      6984080.30
#Sta/Elev= 30
  4501.4 1766.46  4636.3 1762.44  4672.2 1761.51  4777.3 1757.16  4809.0 1757.98
  4814.7 1756.51  4831.0 1758.25  4836.7 1756.83  4853.0 1758.83  4880.6 1757.05
  4896.9 1758.83  4969.0 1758.70  5023.3 1759.62  5028.9 1758.48  5045.4 1759.58
  5051.0 1758.21  5067.5 1759.46  5104.7 1758.16  5117.4 1757.25  5148.5 1758.20
  5161.7 1756.66  5194.6 1757.40  5200.3 1755.88  5229.2 1755.58  5242.0 1753.80
  5242.4 1753.30  5247.0 1753.80  5255.5 1755.23  5364.4 1761.00  5584.4 1763.10
#Mann=9,-1,0
  4501.4   0.035       0  4636.3    0.07       0  4672.2   0.035       0
  4969.0    0.07       0  5104.7   0.035       0  5148.5    0.07       0
  5242.0    0.07       0  5247.0    0.07       0  5255.5   0.035       0
Bank Sta=5242,5247
Exp/Cntr=0.3,0.1

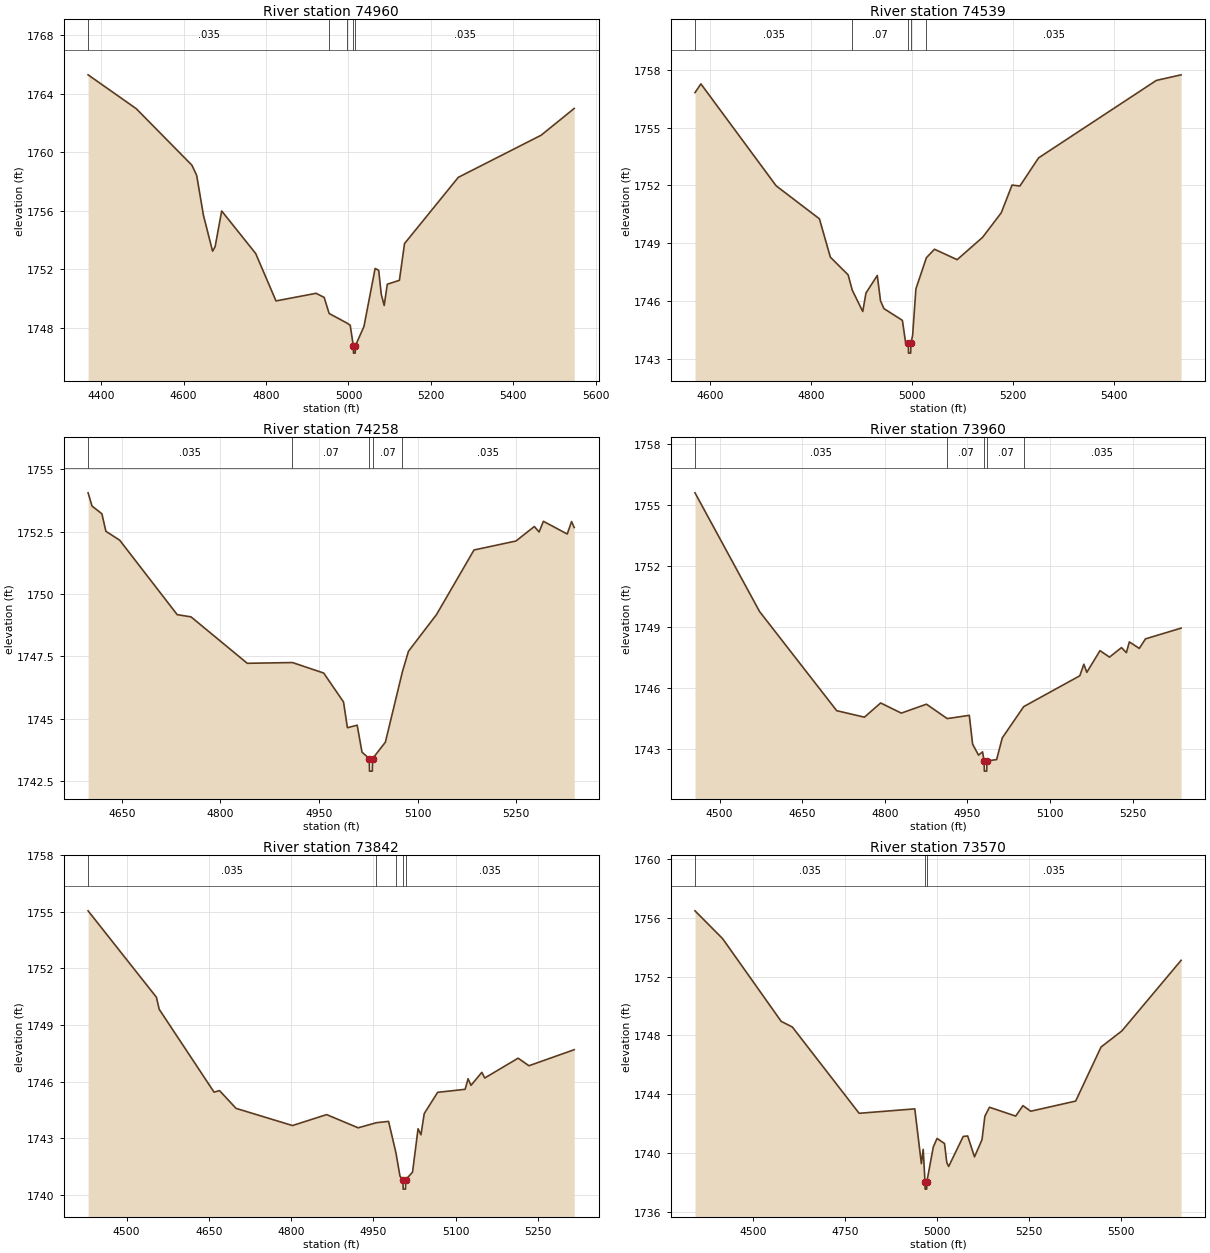
Type RM Length L Ch R = 1,74960,421,421,421
BEGIN DESCRIPTION:
Mapping XS d271404a
END DESCRIPTION:
XS GIS Cut Line= 5
      1685791.50      6983644.22      1686138.73      6983824.35
      1686294.98      6983911.15      1686355.74      6983928.52
      1686800.31      6984245.14
#Sta/Elev= 30
  4368.5 1765.30  4485.1 1762.99  4620.3 1759.12  4631.8 1758.43  4648.3 1755.69
  4670.4 1753.24  4676.6 1753.55  4692.5 1755.99  4775.0 1753.08  4824.2 1749.84
  4921.4 1750.36  4941.0 1750.08  4953.1 1748.98  4995.4 1748.34  5004.2 1748.18
  5011.7 1746.77  5012.1 1746.27  5016.3 1746.27  5016.7 1746.77  5037.5 1748.09
  5064.6 1752.06  5073.3 1751.93  5079.4 1750.31  5086.6 1749.53  5094.1 1750.98
  5123.5 1751.25  5135.9 1753.76  5266.3 1758.29  5467.2 1761.17  5547.4 1763.00
#Mann=5,-1,0
  4368.5   0.035       0  4953.1    0.07       0  4995.4   0.035       0
  5011.7   0.035       0  5016.7   0.035       0
Bank Sta=5011.7,5016.7
Exp/Cntr=0.3,0.1

Type RM Length L Ch R = 1,74539,281,281,281
BEGIN DESCRIPTION:
Mapping XS 33783342
END DESCRIPTION:
XS GIS Cut Line= 3
      1685722.24      6983914.60      1686059.52      6984182.86
      1686515.24      6984456.29
#Sta/Elev= 30
  4570.9 1756.82  4582.6 1757.27  4731.6 1751.98  4817.2 1750.27  4838.9 1748.28
  4874.1 1747.36  4882.2 1746.57  4903.0 1745.46  4909.4 1746.42  4931.8 1747.33
  4938.2 1746.01  4945.0 1745.61  4981.5 1745.00  4987.9 1743.84  4993.3 1743.80
  4993.6 1743.30  4997.9 1743.30  4998.3 1743.80  5001.8 1744.23  5008.2 1746.63
  5029.0 1748.25  5045.0 1748.69  5089.9 1748.15  5140.3 1749.31  5177.2 1750.58
  5198.6 1752.02  5214.1 1751.97  5251.1 1753.43  5484.3 1757.45  5533.3 1757.74
#Mann=5,-1,0
  4570.9   0.035       0  4882.2    0.07       0  4993.3    0.07       0
  4998.3    0.07       0  5029.0   0.035       0
Bank Sta=4993.3,4998.3
Exp/Cntr=0.3,0.1

Type RM Length L Ch R = 1,74258,298,298,298
BEGIN DESCRIPTION:
Mapping XS 13e31329
END DESCRIPTION:
XS GIS Cut Line= 3
      1685675.08      6984010.43      1685896.43      6984347.68
      1686114.14      6984604.26
#Sta/Elev= 30
  4598.5 1754.05  4604.5 1753.52  4619.5 1753.21  4625.6 1752.51  4646.7 1752.15
  4734.1 1749.17  4755.2 1749.08  4840.8 1747.22  4909.6 1747.25  4957.1 1746.83
  4987.3 1745.67  4993.2 1744.64  5008.1 1744.74  5015.4 1743.66  5026.5 1743.40
  5026.8 1742.90  5031.1 1742.90  5031.5 1743.40  5051.0 1744.06  5076.9 1746.88
  5086.1 1747.70  5129.0 1749.18  5185.9 1751.76  5249.8 1752.12  5277.7 1752.70
  5285.0 1752.48  5291.5 1752.91  5327.8 1752.40  5334.4 1752.90  5338.4 1752.66
#Mann=5,-1,0
  4598.5   0.035       0  4909.6    0.07       0  5026.5    0.07       0
  5031.5    0.07       0  5076.9   0.035       0
Bank Sta=5026.5,5031.5
Exp/Cntr=0.3,0.1

Type RM Length L Ch R = 1,73960,118,118,118
BEGIN DESCRIPTION:
Mapping XS 692c0dde
END DESCRIPTION:
XS GIS Cut Line= 4
      1685585.24      6983990.88      1685576.12      6984264.34
      1685677.68      6984515.65      1685806.58      6984828.14
#Sta/Elev= 30
  4455.5 1755.61  4572.7 1749.76  4712.8 1744.87  4763.1 1744.55  4792.6 1745.25
  4830.1 1744.75  4875.8 1745.19  4913.5 1744.48  4953.6 1744.64  4959.6 1743.22
  4970.3 1742.68  4977.7 1742.84  4980.5 1742.39  4980.9 1741.89  4985.2 1741.89
  4985.6 1742.39  5003.2 1742.46  5013.5 1743.53  5052.4 1745.07  5154.2 1746.59
  5161.6 1747.16  5167.0 1746.76  5190.9 1747.83  5208.2 1747.51  5229.9 1747.98
  5238.8 1747.73  5244.2 1748.26  5262.3 1747.94  5273.5 1748.41  5338.2 1748.94
#Mann=5,-1,0
  4455.5   0.035       0  4913.5    0.07       0  4980.5    0.07       0
  4985.6    0.07       0  5052.4   0.035       0
Bank Sta=4980.5,4985.6
Exp/Cntr=0.3,0.1

Type RM Length L Ch R = 1,73842,272,272,272
BEGIN DESCRIPTION:
Mapping XS f40d75bf
END DESCRIPTION:
XS GIS Cut Line= 5
      1685470.65      6983988.27      1685469.35      6984237.00
      1685479.77      6984356.79      1685568.31      6984540.39
      1685677.14      6984834.49
#Sta/Elev= 30
  4429.7 1755.05  4554.3 1750.47  4559.4 1749.83  4659.4 1745.44  4669.4 1745.52
  4699.5 1744.58  4802.4 1743.67  4864.7 1744.25  4922.1 1743.55  4955.4 1743.82
  4977.6 1743.89  4991.1 1742.22  4998.4 1740.99  5003.8 1740.80  5004.2 1740.30
  5008.5 1740.30  5008.9 1740.80  5021.3 1741.20  5031.4 1743.50  5036.7 1743.18
  5042.6 1744.30  5067.1 1745.43  5117.2 1745.59  5122.6 1746.15  5127.9 1745.80
  5147.7 1746.49  5153.0 1746.19  5213.8 1747.24  5233.6 1746.84  5316.1 1747.69
#Mann=5,-1,0
  4429.7   0.035       0  4955.4    0.07       0  4991.1   0.035       0
  5003.8   0.035       0  5008.9   0.035       0
Bank Sta=5003.8,5008.9
Exp/Cntr=0.3,0.1

Type RM Length L Ch R = 1,73570,416,416,416
BEGIN DESCRIPTION:
Mapping XS 5ec9d795
END DESCRIPTION:
XS GIS Cut Line= 3
      1685379.24      6983885.54      1685294.18      6984543.51
      1685169.17      6985189.38
#Sta/Elev= 30
  4342.1 1756.46  4417.2 1754.57  4576.5 1748.95  4606.7 1748.57  4788.2 1742.71
  4939.5 1743.01  4957.4 1739.29  4962.4 1740.26  4967.2 1738.06  4967.6 1737.56
  4971.9 1737.56  4972.3 1738.06  4989.9 1740.43  5000.0 1741.00  5020.3 1740.66
  5026.5 1739.36  5031.6 1739.10  5071.2 1741.14  5083.3 1741.17  5101.8 1739.75
  5122.2 1740.92  5130.0 1742.51  5142.5 1743.12  5213.8 1742.52  5233.6 1743.23
  5254.6 1742.85  5376.8 1743.54  5445.8 1747.21  5502.6 1748.31  5663.4 1753.10
#Mann=3,-1,0
  4342.1   0.035       0  4967.2   0.035       0  4972.3   0.035       0
Bank Sta=4967.2,4972.3
Exp/Cntr=0.3,0.1

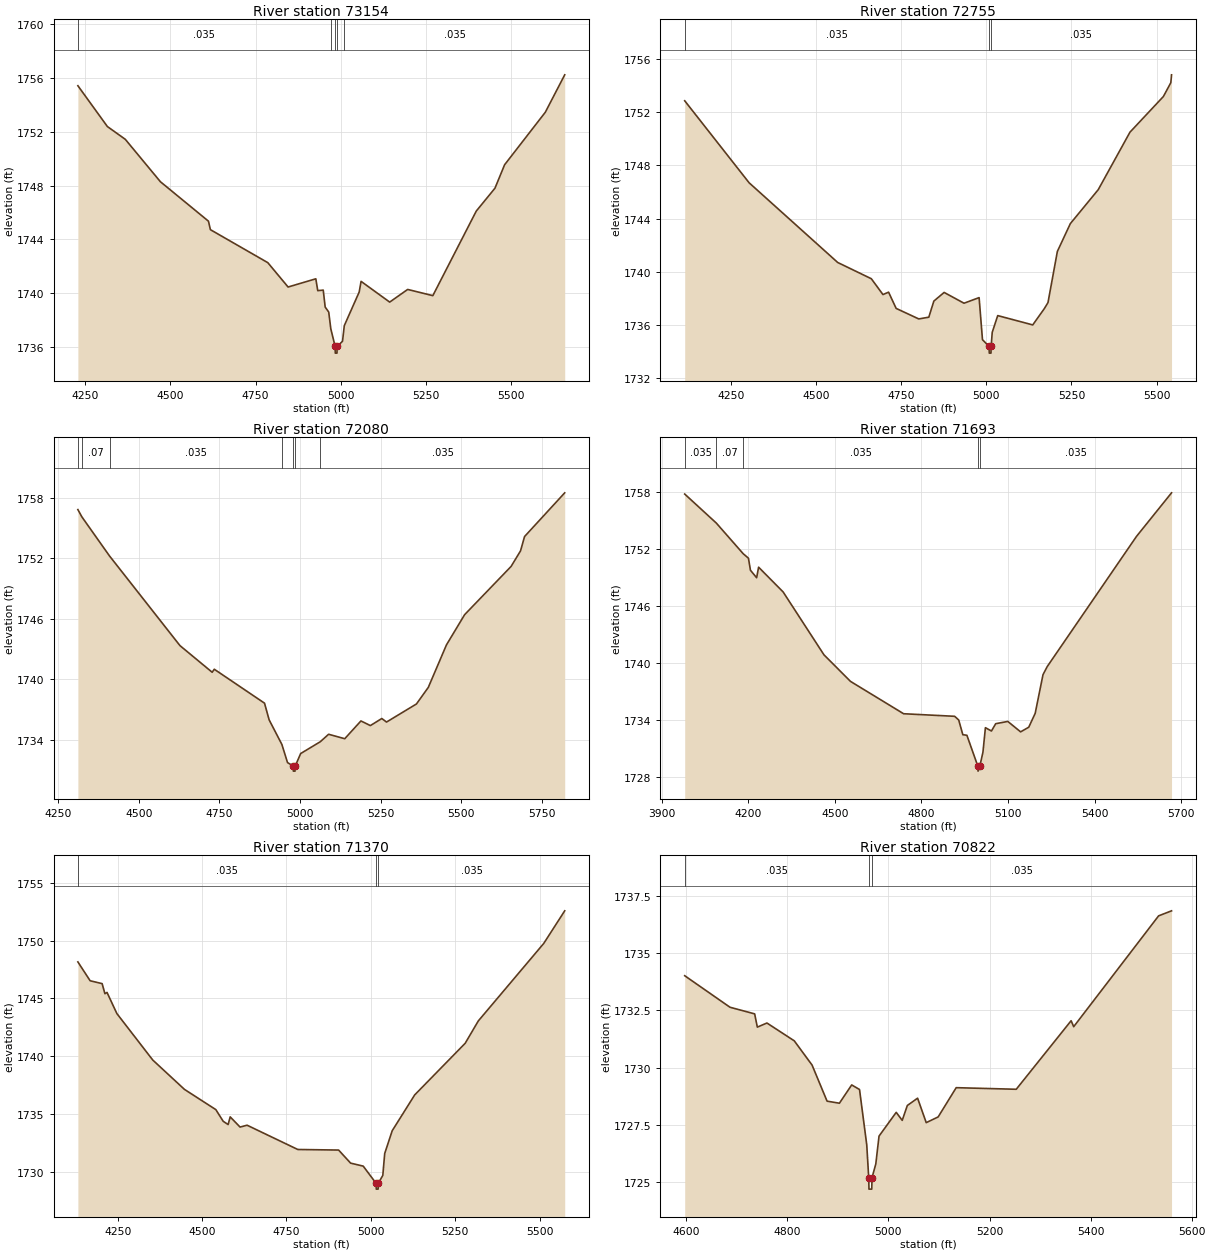
Type RM Length L Ch R = 1,73154,399,399,399
BEGIN DESCRIPTION:
Mapping XS 0bca1b92
END DESCRIPTION:
XS GIS Cut Line= 3
      1685257.72      6983842.12      1684882.72      6984522.68
      1684604.94      6985112.95
#Sta/Elev= 30
  4228.2 1755.41  4314.8 1752.38  4367.4 1751.43  4470.5 1748.28  4611.6 1745.35
  4617.3 1744.72  4785.8 1742.27  4845.4 1740.46  4926.8 1741.07  4932.5 1740.19
  4948.6 1740.23  4954.3 1738.97  4964.7 1738.60  4970.8 1737.36  4983.5 1736.05
  4984.0 1735.55  4989.0 1735.55  4989.5 1736.05  5005.2 1736.43  5010.4 1737.59
  5054.2 1740.09  5059.7 1740.88  5143.7 1739.34  5196.5 1740.28  5270.4 1739.82
  5397.9 1746.10  5452.8 1747.80  5481.1 1749.54  5600.6 1753.44  5657.6 1756.22
#Mann=5,-1,0
  4228.2   0.035       0  4970.8    0.07       0  4983.5    0.07       0
  4989.5    0.07       0  5010.4   0.035       0
Bank Sta=4983.5,4989.5
Exp/Cntr=0.3,0.1

Type RM Length L Ch R = 1,72755,675,675,675
BEGIN DESCRIPTION:
Mapping XS 275eb08d
END DESCRIPTION:
XS GIS Cut Line= 3
      1684934.81      6983651.14      1684526.81      6984441.08
      1684269.94      6984916.65
#Sta/Elev= 30
  4114.4 1752.85  4303.5 1746.69  4563.7 1740.70  4662.4 1739.48  4696.6 1738.29
  4713.1 1738.47  4735.3 1737.25  4801.7 1736.46  4831.2 1736.59  4846.0 1737.80
  4876.2 1738.45  4934.6 1737.64  4978.9 1738.06  4988.8 1734.90  5008.3 1734.39
  5008.8 1733.89  5013.8 1733.89  5014.3 1734.39  5017.4 1735.45  5033.6 1736.71
  5136.4 1736.01  5170.6 1737.24  5181.2 1737.69  5208.7 1741.53  5246.8 1743.62
  5328.7 1746.17  5421.9 1750.49  5520.0 1753.17  5541.9 1754.21  5544.0 1754.80
#Mann=3,-1,0
  4114.4   0.035       0  5008.3   0.035       0  5014.3   0.035       0
Bank Sta=5008.3,5014.3
Exp/Cntr=0.3,0.1

Type RM Length L Ch R = 1,72080,387,387,387
BEGIN DESCRIPTION:
Mapping XS 082400e0
END DESCRIPTION:
XS GIS Cut Line= 3
      1684882.92      6983488.97      1684356.85      6983940.39
      1683872.45      6984598.41
#Sta/Elev= 30
  4310.9 1756.82  4323.5 1756.09  4409.0 1752.23  4627.6 1743.35  4727.5 1740.71
  4734.1 1741.01  4889.9 1737.65  4904.2 1736.00  4943.8 1733.56  4961.2 1731.77
  4978.9 1731.42  4979.4 1730.92  4984.7 1730.92  4985.2 1731.42  5002.0 1732.66
  5062.9 1733.83  5088.7 1734.57  5138.8 1734.13  5189.0 1735.89  5218.3 1735.43
  5253.8 1736.13  5268.4 1735.78  5361.2 1737.57  5398.0 1739.21  5454.3 1743.42
  5510.6 1746.41  5654.8 1751.19  5684.1 1752.73  5696.6 1754.15  5821.2 1758.48
#Mann=7,-1,0
  4310.9   0.035       0  4323.5    0.07       0  4409.0   0.035       0
  4943.8    0.07       0  4978.9    0.07       0  4985.2    0.07       0
  5062.9   0.035       0
Bank Sta=4978.9,4985.2
Exp/Cntr=0.3,0.1

Type RM Length L Ch R = 1,71693,323,323,323
BEGIN DESCRIPTION:
Mapping XS 6da6b12f
END DESCRIPTION:
XS GIS Cut Line= 3
      1684779.22      6983140.07      1684030.98      6983841.43
      1683650.80      6984383.06
#Sta/Elev= 30
  3979.4 1757.81  4089.0 1754.75  4182.1 1751.52  4200.3 1751.05  4207.2 1749.78
  4228.7 1748.99  4235.5 1750.10  4320.5 1747.49  4462.1 1740.86  4554.0 1738.06
  4738.1 1734.65  4914.9 1734.38  4929.1 1733.99  4943.3 1732.44  4957.4 1732.38
  4995.6 1729.10  4996.1 1728.60  5002.0 1729.10  5013.0 1730.59  5021.6 1733.18
  5042.5 1732.83  5057.3 1733.60  5099.2 1733.84  5143.6 1732.74  5171.8 1733.23
  5194.1 1734.69  5221.2 1738.77  5236.0 1739.63  5545.3 1753.35  5666.7 1757.94
#Mann=5,-1,0
  3979.4   0.035       0  4089.0    0.07       0  4182.1   0.035       0
  4995.6   0.035       0  5002.0   0.035       0
Bank Sta=4995.6,5002
Exp/Cntr=0.3,0.1

Type RM Length L Ch R = 1,71370,548,548,548
BEGIN DESCRIPTION:
Mapping XS 4a8cdbe9
END DESCRIPTION:
XS GIS Cut Line= 3
      1684492.57      6983163.94      1683796.39      6983683.03
      1683534.33      6984193.27
#Sta/Elev= 30
  4132.2 1748.16  4168.5 1746.53  4204.0 1746.28  4212.3 1745.41  4218.5 1745.52
  4247.7 1743.69  4354.0 1739.67  4447.9 1737.13  4540.8 1735.38  4562.6 1734.37
  4577.2 1734.09  4583.4 1734.75  4612.6 1733.87  4633.4 1734.03  4783.6 1731.93
  4904.5 1731.88  4940.0 1730.75  4977.4 1730.49  5015.6 1729.00  5016.1 1728.50
  5021.5 1728.50  5022.0 1729.00  5035.4 1729.69  5041.0 1731.58  5063.2 1733.55
  5129.8 1736.65  5279.4 1741.12  5318.2 1743.05  5512.1 1749.76  5574.2 1752.58
#Mann=3,-1,0
  4132.2   0.035       0  5015.6   0.035       0  5022.0   0.035       0
Bank Sta=5015.6,5022
Exp/Cntr=0.3,0.1

Type RM Length L Ch R = 1,70822,436,436,436
BEGIN DESCRIPTION:
Mapping XS bcf524e6
END DESCRIPTION:
XS GIS Cut Line= 3
      1683801.60      6982816.29      1683652.94      6983192.80
      1683556.38      6983742.89
#Sta/Elev= 30
  4596.9 1734.02  4686.5 1732.64  4735.3 1732.35  4740.6 1731.77  4759.6 1731.95
  4813.7 1731.17  4848.9 1730.11  4878.6 1728.53  4903.0 1728.44  4927.3 1729.24
  4942.8 1729.04  4957.1 1726.62  4961.0 1725.18  4961.5 1724.68  4967.0 1724.68
  4967.5 1725.18  4975.0 1725.78  4981.4 1727.00  5015.4 1728.04  5027.3 1727.69
  5037.4 1728.34  5057.7 1728.66  5074.8 1727.59  5098.4 1727.84  5134.1 1729.12
  5252.9 1729.05  5361.5 1732.05  5366.6 1731.79  5534.6 1736.64  5560.2 1736.86
#Mann=3,-1,0
  4596.9   0.035       0  4961.0   0.035       0  4967.5   0.035       0
Bank Sta=4961,4967.5
Exp/Cntr=0.3,0.1