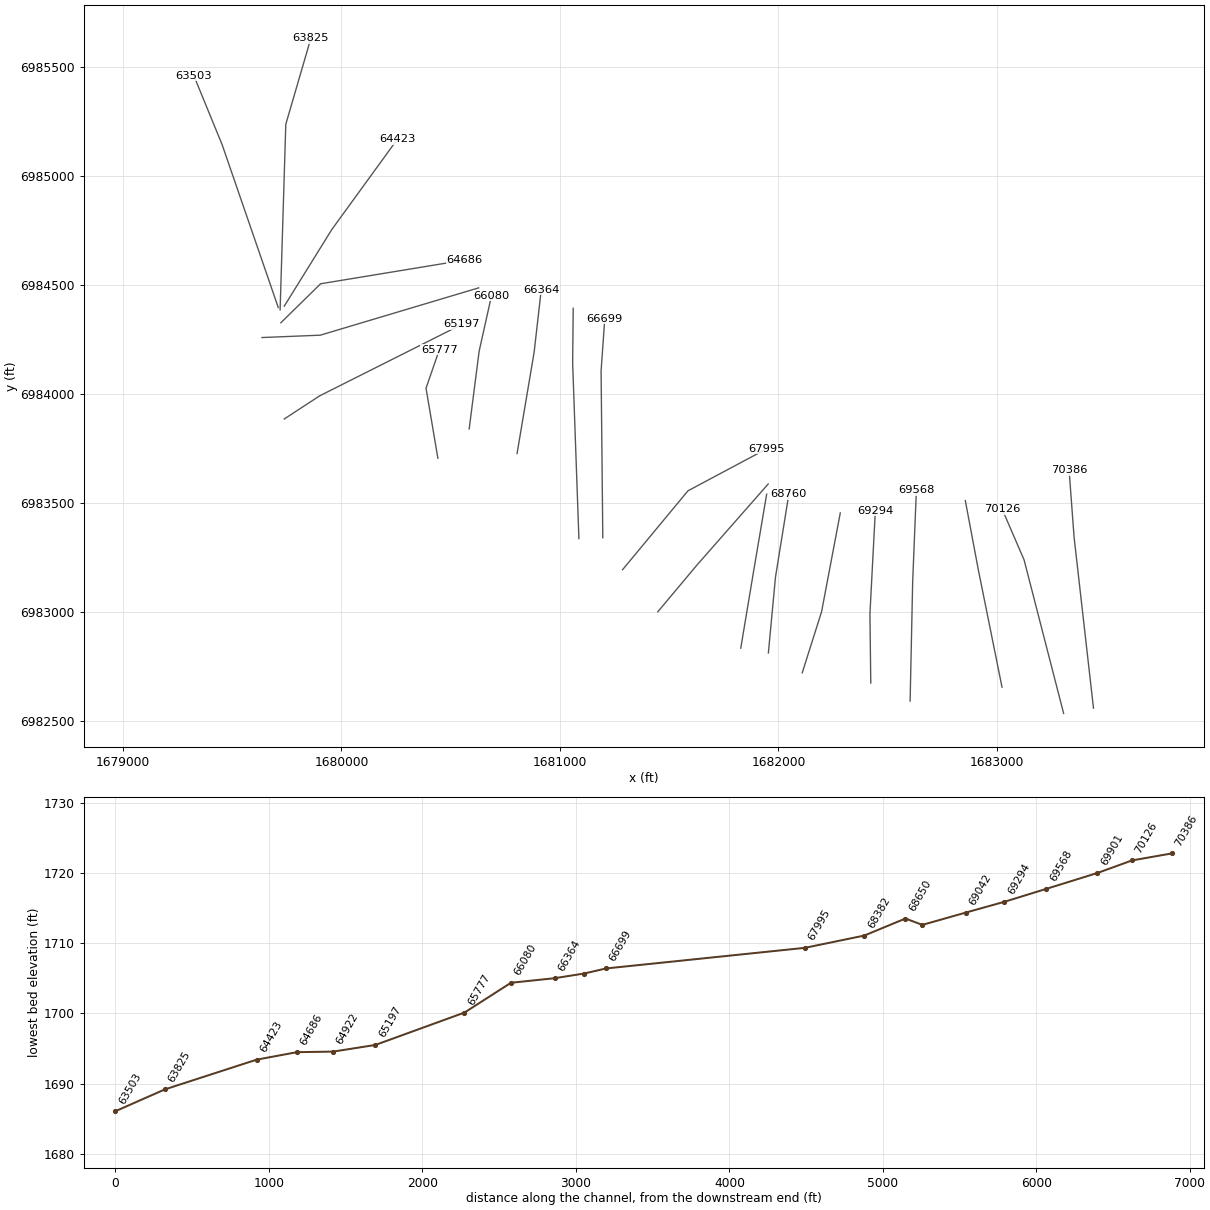
HEC-RAS study Fish Creek.prj: Fish Creek Base Level Engineering

--- Fish Creek.g01 (geometry) --- (continued)

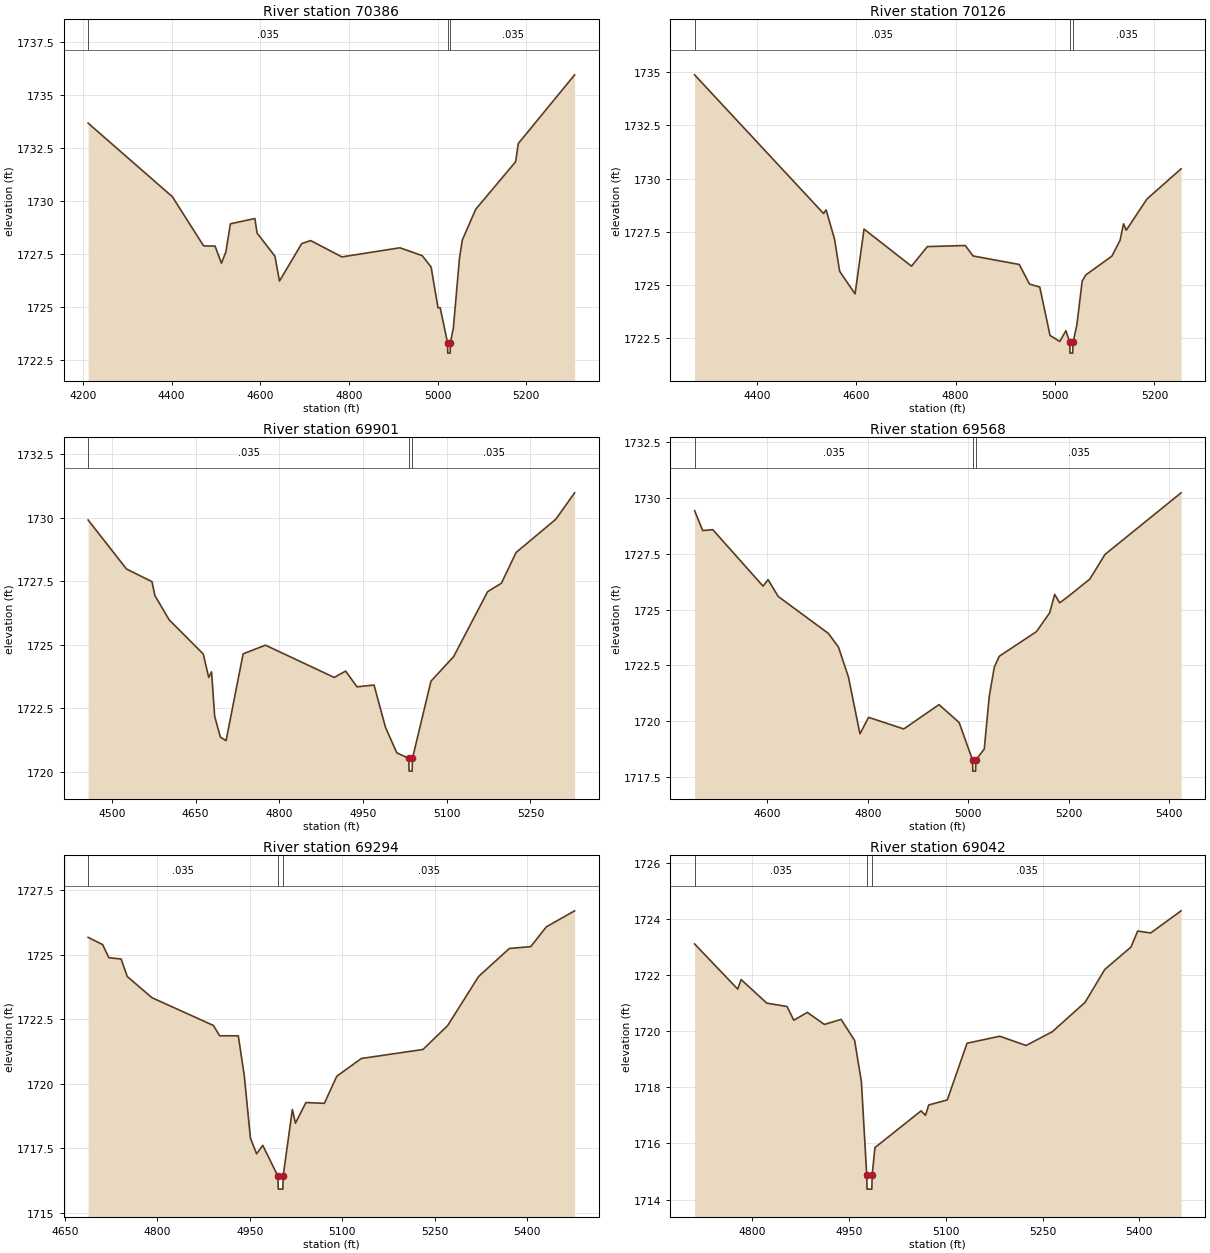
Type RM Length L Ch R = 1,70386,260,260,260
BEGIN DESCRIPTION:
Mapping XS d7463511
END DESCRIPTION:
XS GIS Cut Line= 3
      1683442.32      6982559.17      1683353.46      6983343.62
      1683330.68      6983650.71
#Sta/Elev= 30
  4211.8 1733.66  4401.8 1730.19  4472.3 1727.87  4498.2 1727.86  4512.5 1727.05
  4522.6 1727.59  4532.7 1728.91  4587.9 1729.16  4593.1 1728.47  4633.3 1727.38
  4643.4 1726.21  4693.7 1727.98  4713.8 1728.12  4784.3 1727.35  4915.1 1727.78
  4965.4 1727.41  4985.5 1726.87  5001.0 1724.95  5006.0 1724.95  5022.5 1723.31
  5023.0 1722.81  5028.5 1722.81  5029.0 1723.31  5035.7 1724.00  5049.4 1727.27
  5055.8 1728.14  5085.9 1729.59  5176.1 1731.84  5182.2 1732.70  5309.2 1735.94
#Mann=3,-1,0
  4211.8   0.035       0  5022.5   0.035       0  5029.0   0.035       0
Bank Sta=5022.5,5029
Exp/Cntr=0.3,0.1

Type RM Length L Ch R = 1,70126,225,225,225
BEGIN DESCRIPTION:
Mapping XS 0e177b2d
END DESCRIPTION:
XS GIS Cut Line= 3
      1683305.60      6982535.32      1683124.51      6983239.55
      1683024.69      6983470.67
#Sta/Elev= 30
  4274.8 1734.87  4534.4 1728.36  4539.5 1728.53  4556.4 1727.16  4566.7 1725.65
  4597.7 1724.59  4615.8 1727.63  4711.2 1725.89  4743.2 1726.81  4819.5 1726.86
  4835.1 1726.37  4928.1 1725.97  4948.7 1725.05  4969.4 1724.91  4990.0 1722.64
  5009.5 1722.36  5022.0 1722.86  5029.7 1722.31  5030.2 1721.81  5035.7 1721.81
  5036.2 1722.31  5043.9 1723.12  5054.7 1725.19  5062.0 1725.48  5114.4 1726.36
  5131.0 1727.11  5137.9 1727.88  5143.4 1727.58  5184.9 1729.04  5253.7 1730.46
#Mann=3,-1,0
  4274.8   0.035       0  5029.7   0.035       0  5036.2   0.035       0
Bank Sta=5029.7,5036.2
Exp/Cntr=0.3,0.1

Type RM Length L Ch R = 1,69901,333,333,333
BEGIN DESCRIPTION:
Mapping XS 3341be7b
END DESCRIPTION:
XS GIS Cut Line= 3
      1683023.59      6982655.65      1682915.52      6983192.12
      1682855.63      6983511.10
#Sta/Elev= 30
  4457.4 1729.91  4526.2 1727.98  4571.9 1727.48  4577.0 1726.94  4602.6 1725.98
  4663.8 1724.63  4673.5 1723.71  4678.6 1723.93  4684.2 1722.18  4694.4 1721.36
  4704.6 1721.22  4735.2 1724.64  4775.2 1724.98  4898.4 1723.71  4918.8 1723.96
  4939.2 1723.34  4969.8 1723.41  4990.2 1721.75  5010.6 1720.74  5032.1 1720.52
  5032.6 1720.02  5038.1 1720.02  5038.6 1720.52  5071.7 1723.56  5112.4 1724.53
  5173.4 1727.09  5198.0 1727.42  5224.3 1728.63  5295.5 1729.94  5329.2 1730.98
#Mann=3,-1,0
  4457.4   0.035       0  5032.1   0.035       0  5038.6   0.035       0
Bank Sta=5032.1,5038.6
Exp/Cntr=0.3,0.1

Type RM Length L Ch R = 1,69568,274,274,274
BEGIN DESCRIPTION:
Mapping XS a774f8fe
END DESCRIPTION:
XS GIS Cut Line= 3
      1682603.02      6982591.85      1682614.73      6983140.04
      1682631.66      6983559.28
#Sta/Elev= 30
  4455.6 1729.43  4471.8 1728.54  4491.8 1728.58  4591.8 1726.05  4601.8 1726.34
  4621.8 1725.59  4721.8 1723.93  4741.8 1723.32  4761.8 1721.97  4784.6 1719.43
  4801.8 1720.17  4871.8 1719.65  4941.9 1720.74  4981.9 1719.94  5008.6 1718.26
  5009.1 1717.76  5014.7 1717.76  5015.2 1718.26  5031.9 1718.75  5041.9 1721.12
  5051.9 1722.42  5061.9 1722.91  5135.7 1724.01  5162.0 1724.85  5172.0 1725.68
  5182.0 1725.30  5202.0 1725.64  5242.1 1726.37  5272.1 1727.47  5423.5 1730.23
#Mann=3,-1,0
  4455.6   0.035       0  5008.6   0.035       0  5015.2   0.035       0
Bank Sta=5008.6,5015.2
Exp/Cntr=0.3,0.1

Type RM Length L Ch R = 1,69294,252,252,252
BEGIN DESCRIPTION:
Mapping XS ca67950f
END DESCRIPTION:
XS GIS Cut Line= 3
      1682422.95      6982674.39      1682419.05      6982990.77
      1682443.74      6983463.82
#Sta/Elev= 30
  4687.4 1725.68  4711.0 1725.40  4721.0 1724.89  4741.0 1724.84  4751.0 1724.16
  4791.0 1723.34  4891.0 1722.26  4901.0 1721.86  4931.3 1721.86  4941.0 1720.32
  4951.0 1717.89  4961.0 1717.28  4971.0 1717.61  4995.7 1716.41  4996.2 1715.91
  5003.6 1715.91  5004.1 1716.41  5019.1 1719.00  5024.1 1718.47  5041.1 1719.27
  5071.1 1719.24  5091.2 1720.29  5131.2 1720.98  5231.3 1721.33  5271.4 1722.26
  5321.5 1724.16  5371.5 1725.25  5406.2 1725.32  5431.6 1726.09  5477.5 1726.71
#Mann=3,-1,0
  4687.4   0.035       0  4995.7   0.035       0  5004.1   0.035       0
Bank Sta=4995.7,5004.1
Exp/Cntr=0.3,0.1

Type RM Length L Ch R = 1,69042,282,282,282
BEGIN DESCRIPTION:
Mapping XS e2fd1be4
END DESCRIPTION:
XS GIS Cut Line= 3
      1682109.16      6982721.25      1682197.69      6983001.18
      1682283.39      6983454.35
#Sta/Elev= 30
  4710.2 1723.11  4777.1 1721.50  4782.4 1721.84  4822.2 1721.00  4853.6 1720.88
  4864.1 1720.39  4885.1 1720.67  4911.6 1720.24  4937.5 1720.42  4958.5 1719.67
  4969.0 1718.20  4977.3 1714.87  4977.8 1714.37  4985.2 1714.37  4985.7 1714.87
  4990.0 1715.85  5061.6 1717.16  5068.4 1717.00  5073.5 1717.37  5102.3 1717.55
  5132.9 1719.57  5183.7 1719.82  5224.5 1719.49  5265.2 1719.98  5316.1 1721.03
  5346.6 1722.20  5387.3 1723.00  5397.7 1723.57  5417.8 1723.50  5465.0 1724.29
#Mann=3,-1,0
  4710.2   0.035       0  4977.3   0.035       0  4985.7   0.035       0
Bank Sta=4977.3,4985.7
Exp/Cntr=0.3,0.1

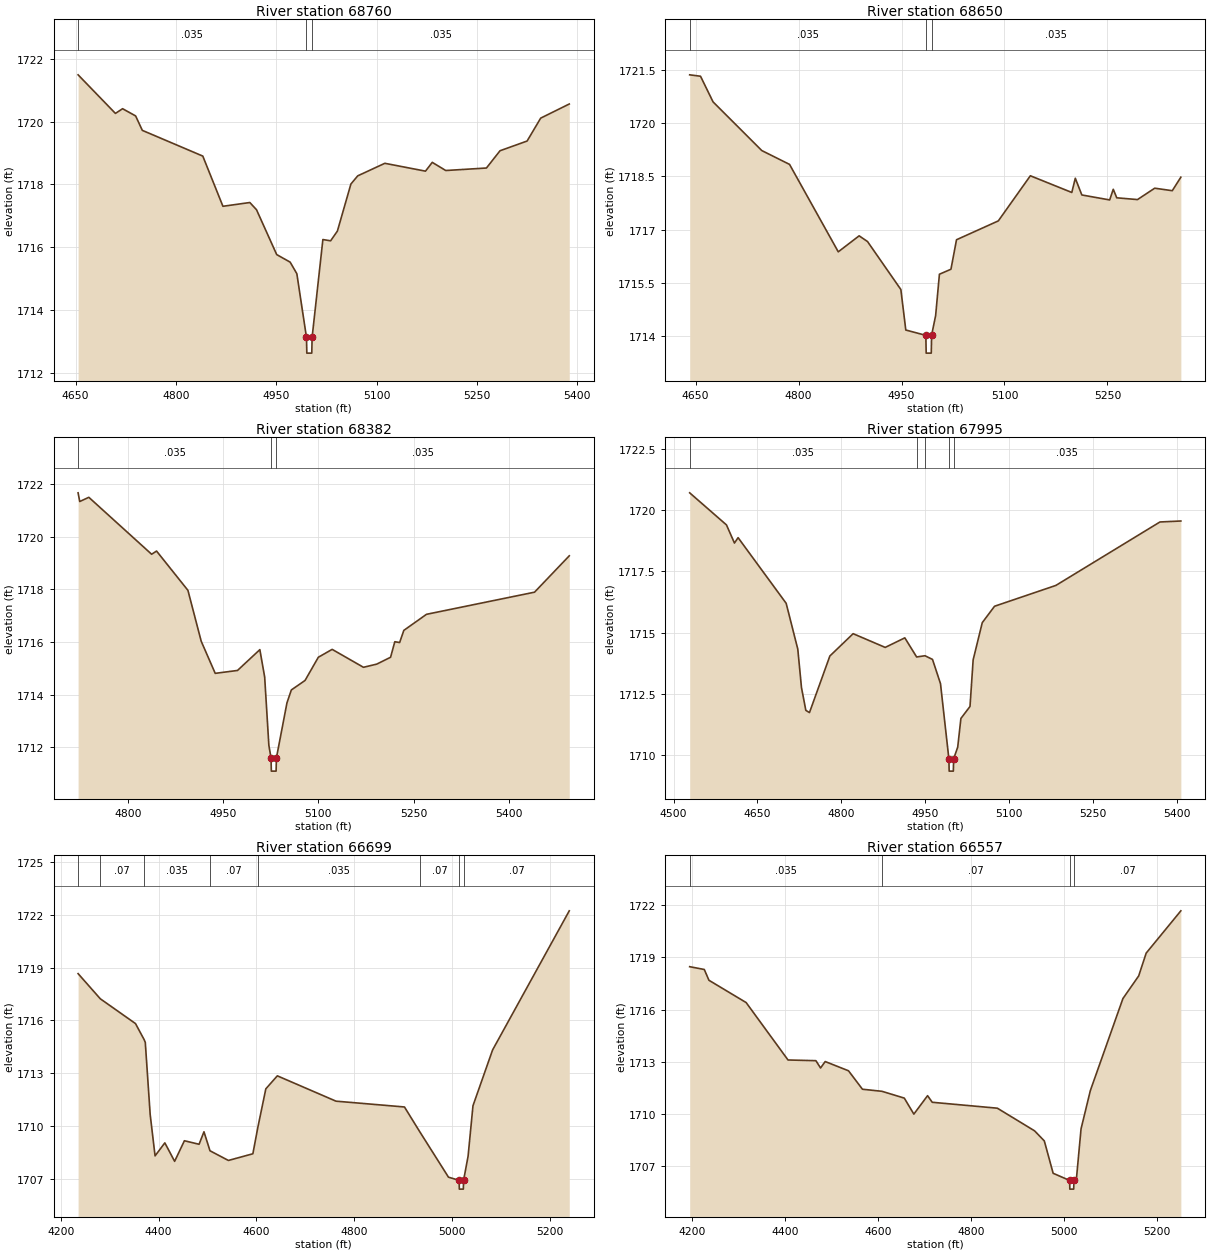
Type RM Length L Ch R = 1,68760,110,110,110
BEGIN DESCRIPTION:
Mapping XS 67716989
END DESCRIPTION:
XS GIS Cut Line= 3
      1681954.21      6982812.42      1681986.75      6983160.04
      1682047.95      6983540.21
#Sta/Elev= 30
  4653.7 1721.49  4709.5 1720.26  4720.2 1720.41  4739.7 1720.18  4749.7 1719.72
  4840.1 1718.90  4870.2 1717.30  4910.4 1717.42  4920.4 1717.19  4950.6 1715.76
  4970.7 1715.52  4980.7 1715.15  4995.1 1713.12  4995.6 1712.62  5003.0 1712.62
  5003.5 1713.12  5019.6 1716.24  5031.2 1716.20  5041.3 1716.51  5061.5 1718.01
  5071.7 1718.27  5112.2 1718.67  5173.0 1718.42  5183.1 1718.70  5203.3 1718.44
  5264.1 1718.52  5284.4 1719.07  5324.9 1719.38  5345.2 1720.11  5387.9 1720.56
#Mann=3,-1,0
  4653.7   0.035       0  4995.1   0.035       0  5003.5   0.035       0
Bank Sta=4995.1,5003.5
Exp/Cntr=0.3,0.1

Type RM Length L Ch R = 1,68650,268,268,268
BEGIN DESCRIPTION:
Mapping XS 216f2440
END DESCRIPTION:
XS GIS Cut Line= 3
      1681827.89      6982834.47      1681887.80      6983193.89
      1681946.40      6983540.29
#Sta/Elev= 30
  4641.3 1721.36  4657.1 1721.32  4675.3 1720.60  4746.3 1719.23  4786.8 1718.84
  4857.8 1716.38  4888.2 1716.83  4900.4 1716.67  4949.0 1715.32  4956.2 1714.18
  4985.4 1714.03  4985.9 1713.53  4993.3 1713.53  4993.8 1714.03  4999.7 1714.59
  5005.2 1715.75  5022.0 1715.89  5030.1 1716.72  5091.0 1717.25  5137.7 1718.52
  5198.1 1718.05  5203.2 1718.45  5212.7 1717.98  5253.3 1717.84  5258.5 1718.14
  5263.6 1717.90  5293.8 1717.85  5318.9 1718.17  5344.5 1718.10  5357.0 1718.48
#Mann=3,-1,0
  4641.3   0.035       0  4985.4   0.035       0  4993.8   0.035       0
Bank Sta=4985.4,4993.8
Exp/Cntr=0.3,0.1

Type RM Length L Ch R = 1,68382,387,387,387
BEGIN DESCRIPTION:
Mapping XS 91ad8dc8
END DESCRIPTION:
XS GIS Cut Line= 3
      1681448.21      6983001.18      1681627.90      6983216.03
      1681953.41      6983587.11
#Sta/Elev= 30
  4721.5 1721.66  4724.1 1721.33  4738.4 1721.49  4837.3 1719.33  4845.1 1719.45
  4894.5 1717.96  4915.4 1716.03  4937.5 1714.81  4972.6 1714.92  5007.8 1715.71
  5015.4 1714.67  5022.0 1712.08  5025.4 1711.60  5025.9 1711.10  5033.4 1711.10
  5033.9 1711.60  5050.5 1713.69  5057.4 1714.18  5079.0 1714.54  5099.9 1715.42
  5121.7 1715.72  5171.0 1715.04  5191.9 1715.16  5213.7 1715.42  5220.4 1716.01
  5228.0 1715.98  5234.6 1716.44  5270.3 1717.05  5440.5 1717.89  5495.2 1719.27
#Mann=3,-1,0
  4721.5   0.035       0  5025.4   0.035       0  5033.9   0.035       0
Bank Sta=5025.4,5033.9
Exp/Cntr=0.3,0.1

Type RM Length L Ch R = 1,67995,1296,1296,1296
BEGIN DESCRIPTION:
Mapping XS b93ab96b
END DESCRIPTION:
XS GIS Cut Line= 3
      1681286.75      6983193.88      1681586.23      6983555.87
      1681946.87      6983748.56
#Sta/Elev= 30
  4528.9 1720.71  4594.7 1719.40  4609.0 1718.66  4615.5 1718.88  4701.5 1716.20
  4722.3 1714.33  4728.9 1712.76  4736.7 1711.83  4743.2 1711.74  4779.7 1714.05
  4821.3 1714.96  4878.7 1714.40  4913.8 1714.79  4934.9 1714.01  4949.8 1714.06
  4963.3 1713.91  4977.6 1712.92  4992.6 1709.85  4993.1 1709.35  5000.6 1709.35
  5001.1 1709.85  5008.4 1710.33  5014.1 1711.50  5030.4 1711.99  5036.0 1713.89
  5052.3 1715.41  5074.3 1716.08  5184.0 1716.93  5370.2 1719.52  5407.6 1719.56
#Mann=5,-1,0
  4528.9   0.035       0  4934.9    0.07       0  4949.8   0.035       0
  4992.6   0.035       0  5001.1   0.035       0
Bank Sta=4992.6,5001.1
Exp/Cntr=0.3,0.1

Type RM Length L Ch R = 1,66699,142,142,142
BEGIN DESCRIPTION:
Mapping XS 39babee8
END DESCRIPTION:
XS GIS Cut Line= 4
      1681196.37      6983340.60      1681192.46      6983726.01
      1681188.56      6984104.92      1681205.38      6984344.37
#Sta/Elev= 30
  4235.5 1718.66  4280.9 1717.23  4352.9 1715.82  4370.7 1714.90  4372.9 1714.75
  4382.9 1710.65  4392.9 1708.30  4412.9 1709.04  4432.9 1707.99  4452.9 1709.16
  4482.9 1708.96  4492.9 1709.67  4505.2 1708.59  4542.9 1708.04  4592.9 1708.42
  4603.0 1709.91  4619.4 1712.11  4642.9 1712.85  4762.9 1711.41  4902.9 1711.08
  4934.0 1709.68  4992.9 1707.09  5014.6 1706.91  5015.1 1706.41  5023.3 1706.41
  5023.8 1706.91  5033.0 1708.28  5043.0 1711.15  5083.1 1714.32  5239.9 1722.23
#Mann=8,-1,0
  4235.5   0.035       0  4280.9    0.07       0  4370.7   0.035       0
  4505.2    0.07       0  4603.0   0.035       0  4934.0    0.07       0
  5014.6    0.07       0  5023.8    0.07       0
Bank Sta=5014.6,5023.8
Exp/Cntr=0.3,0.1

Type RM Length L Ch R = 1,66557,193,193,193
BEGIN DESCRIPTION:
Mapping XS 2d1221db
END DESCRIPTION:
XS GIS Cut Line= 3
      1681086.99      6983336.67      1681058.35      6984141.37
      1681060.95      6984392.64
#Sta/Elev= 30
  4194.9 1718.47  4226.3 1718.31  4236.3 1717.69  4316.3 1716.41  4406.4 1713.11
  4466.4 1713.07  4476.4 1712.65  4486.4 1713.02  4536.5 1712.49  4566.5 1711.43
  4608.5 1711.31  4656.5 1710.92  4677.1 1710.00  4706.6 1711.06  4716.6 1710.68
  4856.7 1710.34  4936.7 1709.04  4957.7 1708.46  4976.7 1706.60  5012.1 1706.19
  5012.6 1705.69  5020.9 1705.69  5021.4 1706.19  5026.7 1706.26  5036.7 1709.15
  5056.7 1711.35  5126.8 1716.64  5160.7 1717.94  5176.8 1719.25  5251.4 1721.68
#Mann=4,-1,0
  4194.9   0.035       0  4608.5    0.07       0  5012.1    0.07       0
  5021.4    0.07       0
Bank Sta=5012.1,5021.4
Exp/Cntr=0.3,0.1

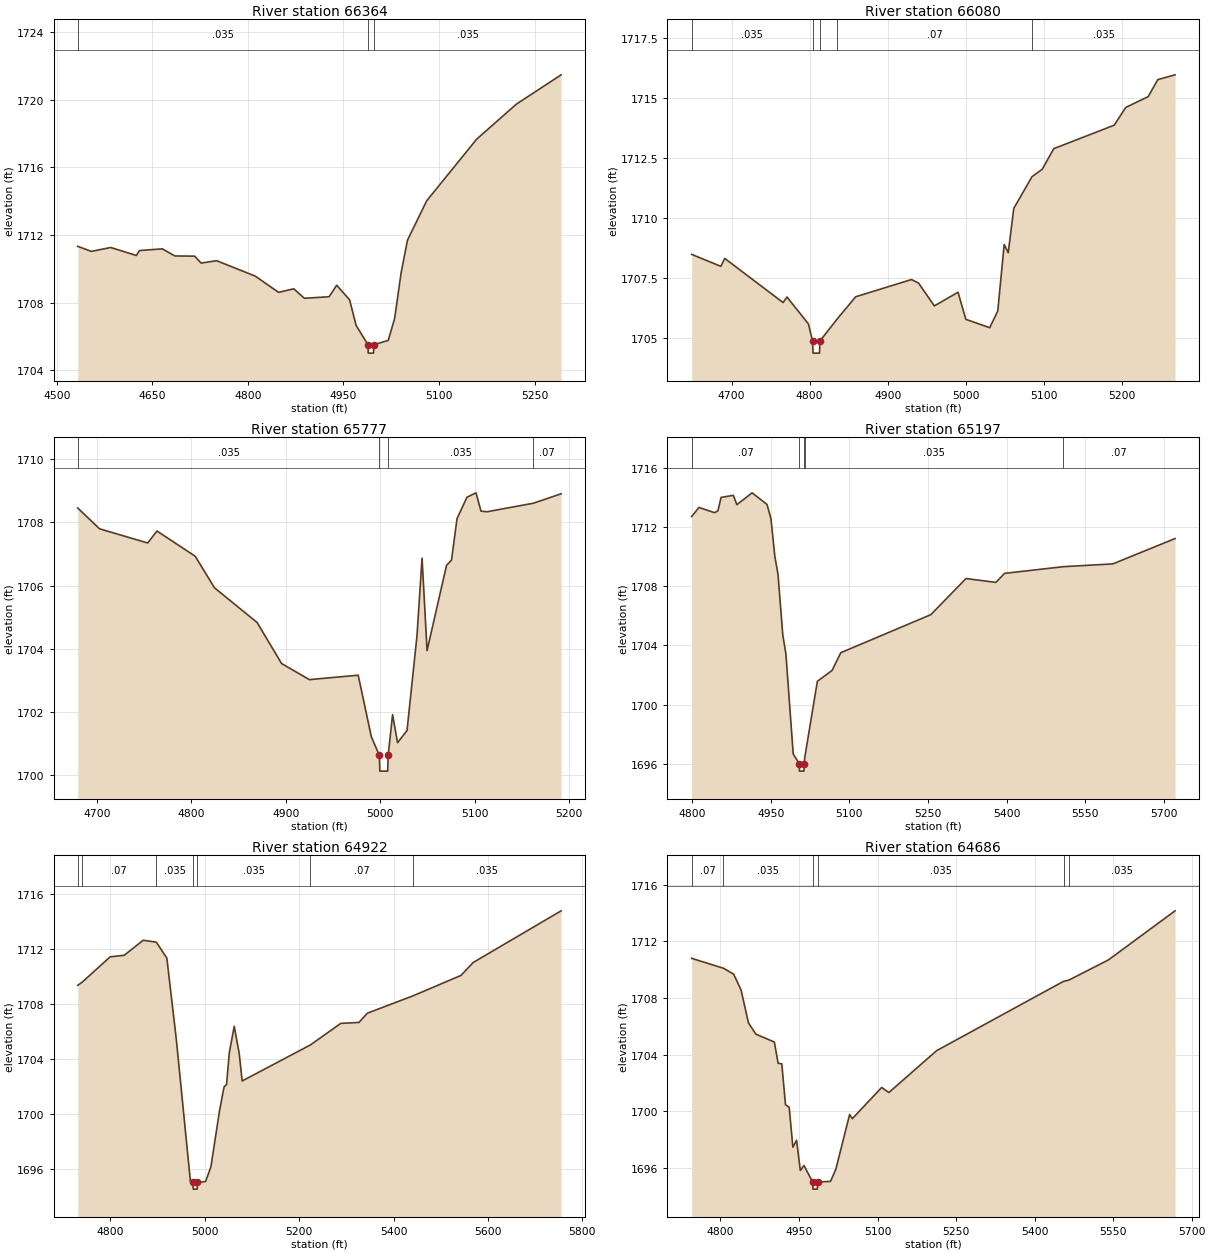
Type RM Length L Ch R = 1,66364,284,284,284
BEGIN DESCRIPTION:
Mapping XS b43a98d5
END DESCRIPTION:
XS GIS Cut Line= 3
      1680803.95      6983726.90      1680882.08      6984191.32
      1680914.63      6984477.73
#Sta/Elev= 30
  4532.6 1711.33  4554.0 1711.03  4584.4 1711.26  4624.6 1710.79  4629.7 1711.08
  4665.5 1711.18  4685.2 1710.76  4716.2 1710.75  4726.4 1710.34  4750.8 1710.48
  4811.4 1709.57  4848.1 1708.61  4871.9 1708.82  4888.6 1708.26  4927.4 1708.35
  4939.3 1709.03  4959.6 1708.17  4969.8 1706.66  4988.4 1705.52  4988.9 1705.02
  4997.2 1705.02  4997.7 1705.52  5020.3 1705.77  5030.4 1707.08  5040.5 1709.76
  5050.5 1711.69  5080.7 1714.02  5159.2 1717.66  5221.6 1719.73  5291.8 1721.46
#Mann=3,-1,0
  4532.6   0.035       0  4988.4   0.035       0  4997.7   0.035       0
Bank Sta=4988.4,4997.7
Exp/Cntr=0.3,0.1

Type RM Length L Ch R = 1,66080,303,303,303
BEGIN DESCRIPTION:
Mapping XS 726b9c9b
END DESCRIPTION:
XS GIS Cut Line= 3
      1680584.77      6983839.71      1680630.34      6984195.66
      1680686.78      6984449.61
#Sta/Elev= 30
  4648.9 1708.49  4686.3 1707.99  4691.3 1708.32  4766.0 1706.48  4771.0 1706.71
  4798.4 1705.59  4803.8 1704.87  4804.3 1704.37  4812.6 1704.37  4813.1 1704.87
  4834.9 1705.78  4858.9 1706.72  4930.4 1707.44  4939.5 1707.29  4959.7 1706.34
  4990.0 1706.91  5000.0 1705.78  5030.6 1705.43  5040.9 1706.13  5049.1 1708.90
  5054.3 1708.56  5061.4 1710.41  5084.7 1711.73  5097.8 1712.04  5112.6 1712.90
  5190.0 1713.88  5204.8 1714.62  5233.5 1715.07  5245.8 1715.78  5267.9 1715.98
#Mann=5,-1,0
  4648.9   0.035       0  4803.8    0.07       0  4813.1   0.035       0
  4834.9    0.07       0  5084.7   0.035       0
Bank Sta=4803.8,4813.1
Exp/Cntr=0.3,0.1

Type RM Length L Ch R = 1,65777,580,580,580
BEGIN DESCRIPTION:
Mapping XS 4ce5f113
END DESCRIPTION:
XS GIS Cut Line= 3
      1680441.54      6983705.25      1680387.29      6984026.39
      1680448.06      6984202.19
#Sta/Elev= 30
  4679.6 1708.46  4702.7 1707.80  4753.7 1707.35  4763.5 1707.73  4804.0 1706.93
  4824.4 1705.93  4869.5 1704.83  4895.4 1703.53  4924.8 1703.02  4976.5 1703.16
  4990.4 1701.21  4998.9 1700.62  4999.4 1700.12  5007.7 1700.12  5008.2 1700.62
  5012.9 1701.91  5018.2 1701.02  5028.2 1701.41  5038.7 1704.40  5044.1 1706.87
  5049.4 1703.94  5070.0 1706.64  5075.3 1706.81  5081.1 1708.12  5091.6 1708.80
  5101.2 1708.94  5106.5 1708.36  5112.8 1708.34  5161.9 1708.61  5191.3 1708.91
#Mann=4,-1,0
  4679.6   0.035       0  4998.9   0.035       0  5008.2   0.035       0
  5161.9    0.07       0
Bank Sta=4998.9,5008.2
Exp/Cntr=0.3,0.1

Type RM Length L Ch R = 1,65197,275,275,275
BEGIN DESCRIPTION:
Mapping XS 62b81a60
END DESCRIPTION:
XS GIS Cut Line= 3
      1679738.44      6983885.34      1679901.18      6983991.66
      1680551.11      6984318.79
#Sta/Elev= 30
  4799.2 1712.71  4813.1 1713.32  4842.9 1712.97  4849.3 1713.09  4855.3 1714.00
  4878.7 1714.14  4885.5 1713.51  4914.5 1714.31  4942.8 1713.53  4950.4 1712.58
  4957.9 1710.01  4963.9 1708.81  4973.0 1704.72  4979.0 1703.42  4992.9 1696.67
  5004.4 1696.01  5004.9 1695.51  5013.3 1695.51  5013.8 1696.01  5014.9 1696.42
  5039.0 1701.58  5067.0 1702.31  5083.7 1703.51  5255.4 1706.08  5322.5 1708.52
  5379.4 1708.26  5396.1 1708.87  5508.0 1709.32  5602.6 1709.51  5721.2 1711.22
#Mann=5,-1,0
  4799.2    0.07       0  5004.4    0.07       0  5013.8    0.07       0
  5014.9   0.035       0  5508.0    0.07       0
Bank Sta=5004.4,5013.8
Exp/Cntr=0.3,0.1

Type RM Length L Ch R = 1,64922,236,236,236
BEGIN DESCRIPTION:
Mapping XS 031eb98e
END DESCRIPTION:
XS GIS Cut Line= 3
      1679636.38      6984258.59      1679903.35      6984269.44
      1680628.17      6984486.45
#Sta/Elev= 30
  4731.1 1709.39  4740.6 1709.62  4799.8 1711.46  4829.8 1711.58  4869.8 1712.67
  4897.6 1712.53  4919.9 1711.37  4939.9 1705.47  4969.9 1695.09  4975.2 1695.06
  4975.7 1694.56  4984.1 1694.56  4984.6 1695.06  5001.8 1695.11  5013.2 1696.18
  5031.3 1700.23  5041.1 1702.00  5046.3 1702.17  5052.2 1704.49  5062.6 1706.41
  5073.1 1704.45  5079.4 1702.43  5223.8 1705.05  5288.3 1706.62  5326.7 1706.69
  5344.5 1707.36  5441.7 1708.63  5542.8 1710.11  5568.7 1711.05  5754.9 1714.81
#Mann=7,-1,0
  4731.1   0.035       0  4740.6    0.07       0  4897.6   0.035       0
  4975.2   0.035       0  4984.6   0.035       0  5223.8    0.07       0
  5441.7   0.035       0
Bank Sta=4975.2,4984.6
Exp/Cntr=0.3,0.1

Type RM Length L Ch R = 1,64686,263,263,263
BEGIN DESCRIPTION:
Mapping XS 2f75cc52
END DESCRIPTION:
XS GIS Cut Line= 3
      1679722.91      6984326.56      1679904.98      6984505.24
      1680564.40      6984613.85
#Sta/Elev= 30
  4744.9 1710.80  4805.7 1710.10  4825.2 1709.68  4839.3 1708.56  4853.5 1706.23
  4867.6 1705.44  4902.9 1704.88  4910.1 1703.38  4917.1 1703.34  4924.2 1700.45
  4931.2 1700.27  4938.3 1697.44  4945.3 1697.94  4952.5 1695.80  4959.5 1696.15
  4976.1 1694.98  4976.6 1694.48  4985.0 1694.48  4985.5 1694.98  5010.2 1695.03
  5020.3 1695.88  5046.7 1699.76  5051.8 1699.46  5107.9 1701.67  5121.6 1701.31
  5212.8 1704.27  5455.6 1709.18  5465.4 1709.26  5541.1 1710.69  5668.3 1714.16
#Mann=6,-1,0
  4744.9    0.07       0  4805.7   0.035       0  4976.1   0.035       0
  4985.5   0.035       0  5455.6    0.07       0  5465.4   0.035       0
Bank Sta=4976.1,4985.5
Exp/Cntr=0.3,0.1

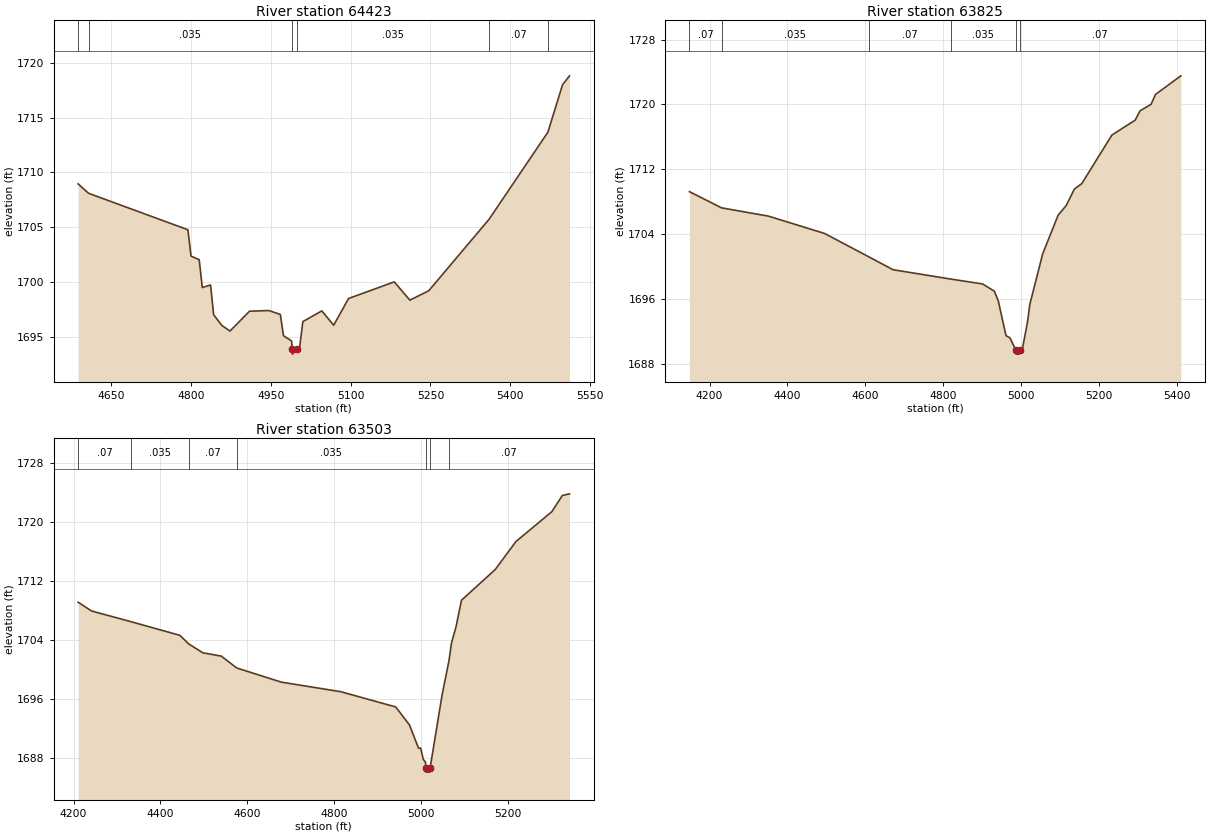
Type RM Length L Ch R = 1,64423,598,598,598
BEGIN DESCRIPTION:
Mapping XS 1173a554
END DESCRIPTION:
XS GIS Cut Line= 3
      1679738.41      6984402.47      1679955.28      6984752.77
      1680255.33      6985166.77
#Sta/Elev= 30
  4588.0 1708.96  4607.7 1708.10  4794.3 1704.77  4800.2 1702.36  4815.5 1702.04
  4821.4 1699.49  4836.8 1699.73  4842.7 1697.01  4858.1 1696.03  4873.4 1695.52
  4910.1 1697.33  4946.7 1697.39  4968.0 1697.03  4973.9 1695.09  4989.2 1694.61
  4990.2 1693.91  4990.7 1693.41  4999.7 1693.91  5004.2 1694.01  5010.3 1696.38
  5045.9 1697.36  5068.2 1696.05  5096.2 1698.49  5182.0 1700.01  5211.4 1698.34
  5246.9 1699.20  5360.4 1705.74  5470.7 1713.68  5498.3 1718.02  5511.3 1718.83
#Mann=6,-1,0
  4588.0    0.07       0  4607.7   0.035       0  4990.2   0.035       0
  4999.7   0.035       0  5360.4    0.07       0  5470.7   0.035       0
Bank Sta=4990.2,4999.7
Exp/Cntr=0.3,0.1

Type RM Length L Ch R = 1,63825,322,322,322
BEGIN DESCRIPTION:
Mapping XS d04c6b75
END DESCRIPTION:
XS GIS Cut Line= 3
      1679719.41      6984385.49      1679745.46      6985236.59
      1679860.18      6985630.53
#Sta/Elev= 30
  4148.5 1709.23  4230.9 1707.23  4351.1 1706.21  4495.3 1704.07  4609.2 1701.18
  4671.3 1699.59  4819.1 1698.44  4901.4 1697.83  4931.4 1696.94  4941.4 1695.76
  4961.4 1691.45  4971.4 1691.18  4986.6 1689.67  4987.1 1689.17  4995.7 1689.17
  4996.2 1689.67  5003.3 1689.78  5016.7 1693.17  5022.3 1695.27  5055.4 1701.53
  5095.2 1706.33  5116.0 1707.52  5136.9 1709.55  5155.9 1710.22  5233.3 1716.22
  5293.1 1718.06  5305.5 1719.21  5333.8 1720.01  5345.2 1721.23  5410.3 1723.53
#Mann=6,-1,0
  4148.5    0.07       0  4230.9   0.035       0  4609.2    0.07       0
  4819.1   0.035       0  4986.6    0.07       0  4996.2    0.07       0
Bank Sta=4986.6,4996.2
Exp/Cntr=0.3,0.1

Type RM Length L Ch R = 1,63503,363,363,363
BEGIN DESCRIPTION:
Mapping XS dd53d4fc
END DESCRIPTION:
XS GIS Cut Line= 3
      1679710.95      6984396.13      1679454.16      6985142.59
      1679324.36      6985459.76
#Sta/Elev= 30
  4210.6 1709.08  4241.6 1707.89  4332.9 1706.43  4445.2 1704.59  4465.2 1703.44
  4498.1 1702.22  4540.4 1701.78  4576.0 1700.17  4678.9 1698.25  4815.4 1696.96
  4942.3 1694.89  4974.0 1692.46  4994.9 1689.31  5000.0 1689.31  5005.7 1687.80
  5011.1 1687.39  5011.8 1686.56  5012.3 1686.06  5020.9 1686.06  5021.4 1686.56
  5049.1 1696.48  5065.2 1701.20  5070.7 1703.51  5081.5 1705.80  5093.9 1709.35
  5171.4 1713.49  5219.4 1717.30  5302.2 1721.35  5326.2 1723.53  5342.7 1723.76
#Mann=7,-1,0
  4210.6    0.07       0  4332.9   0.035       0  4465.2    0.07       0
  4576.0   0.035       0  5011.8   0.035       0  5021.4   0.035       0
  5065.2    0.07       0
Bank Sta=5011.8,5021.4
Exp/Cntr=0.3,0.1