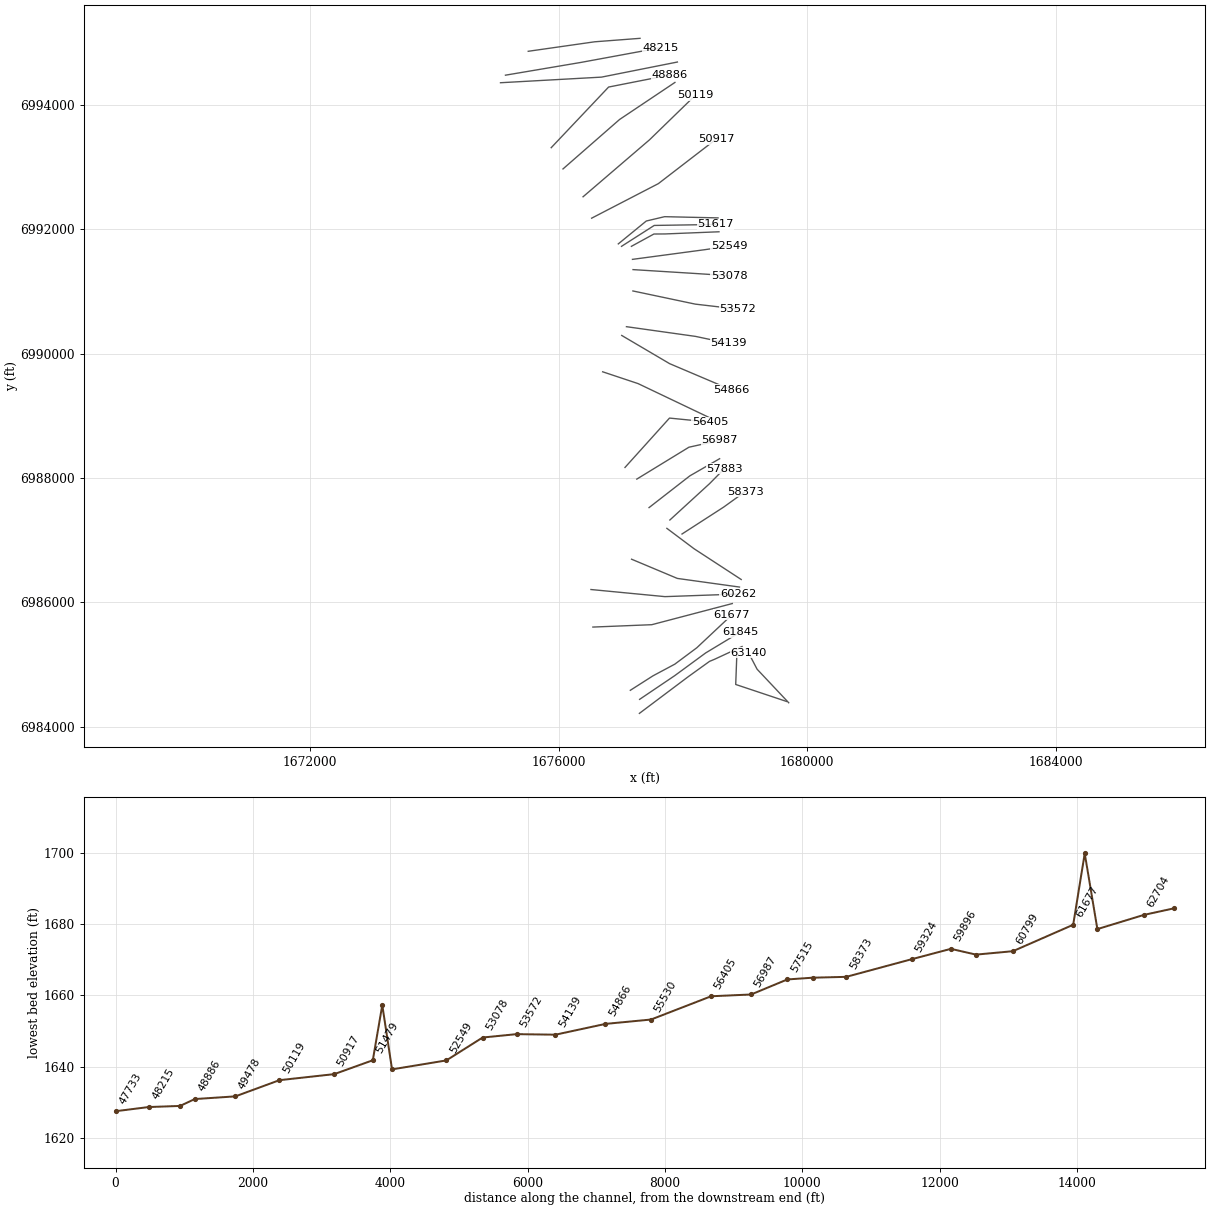
HEC-RAS study Fish Creek.prj: Fish Creek Base Level Engineering

--- Fish Creek.g01 (geometry) --- (continued)

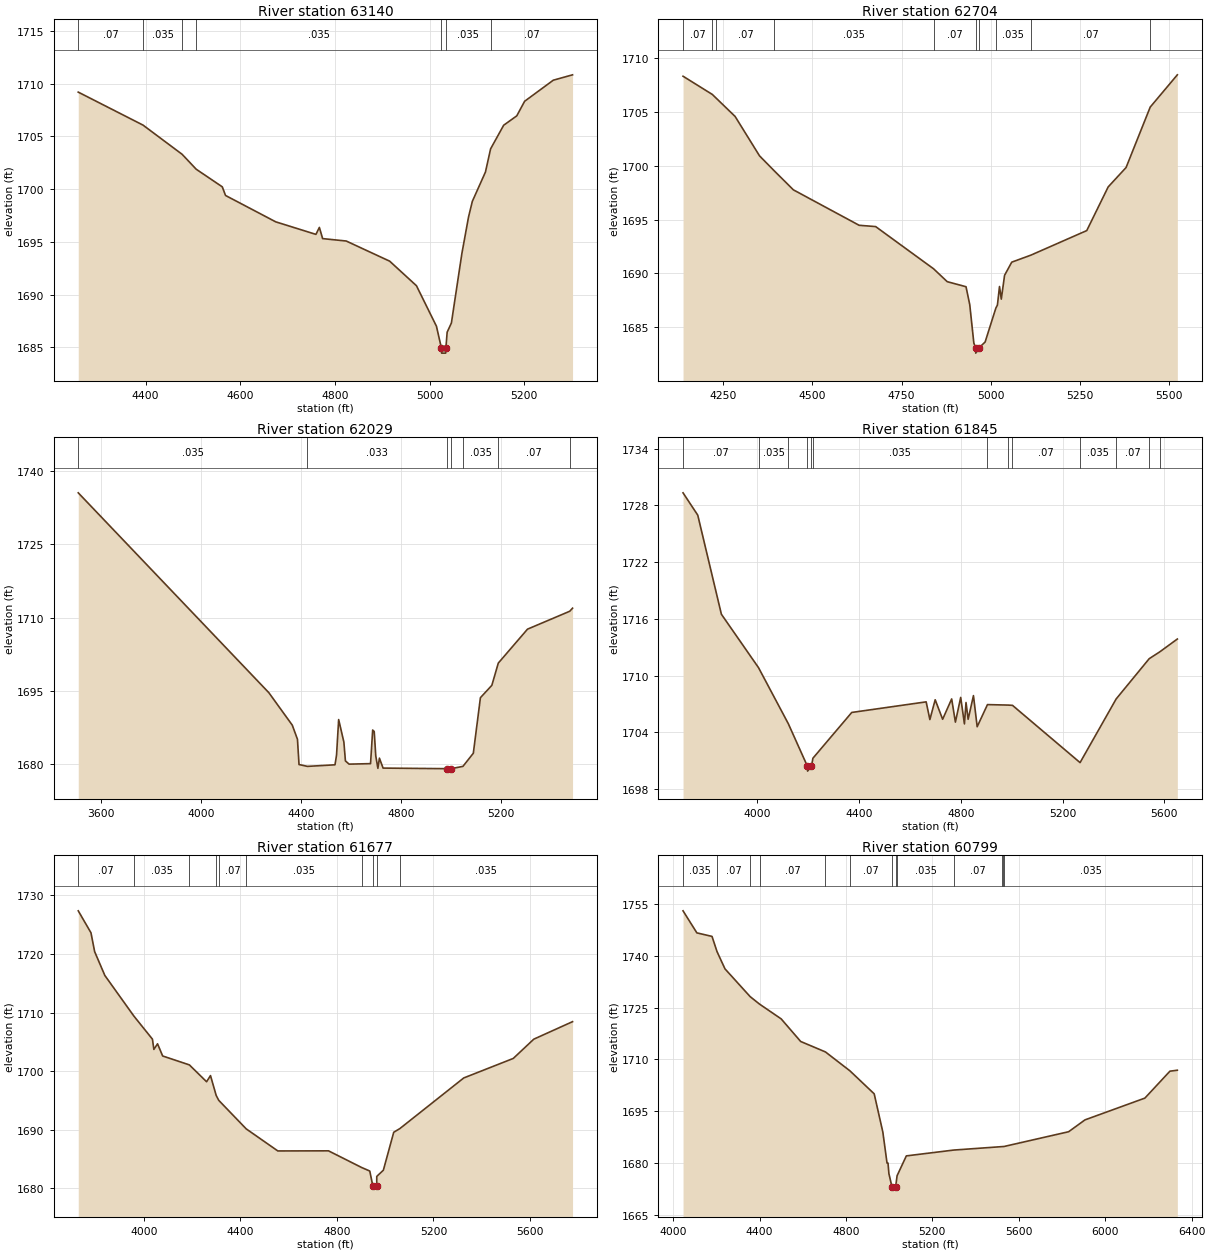
Type RM Length L Ch R = 1,63140,436,436,436
BEGIN DESCRIPTION:
Mapping XS 28e11744
END DESCRIPTION:
XS GIS Cut Line= 3
      1679701.89      6984385.08      1679192.82      6984925.33
      1679053.09      6985192.83
#Sta/Elev= 30
  4257.7 1709.20  4394.6 1706.07  4477.2 1703.30  4506.8 1701.89  4561.9 1700.22
  4568.8 1699.40  4674.8 1696.90  4759.7 1695.71  4767.0 1696.37  4773.9 1695.31
  4823.7 1695.08  4915.5 1693.17  4972.1 1690.84  5014.3 1687.00  5024.7 1684.95
  5025.2 1684.45  5033.8 1684.45  5034.3 1684.95  5036.9 1686.43  5045.9 1687.31
  5068.0 1693.89  5082.0 1697.34  5090.1 1698.84  5117.8 1701.62  5128.7 1703.82
  5156.3 1706.06  5184.0 1706.95  5200.5 1708.33  5261.1 1710.33  5301.8 1710.84
#Mann=7,-1,0
  4257.7    0.07       0  4394.6   0.035       0  4477.2    0.07       0
  4506.8   0.035       0  5024.7   0.035       0  5034.3   0.035       0
  5128.7    0.07       0
Bank Sta=5024.7,5034.3
Exp/Cntr=0.3,0.1

Type RM Length L Ch R = 1,62704,675,675,675
BEGIN DESCRIPTION:
Fish Creek 105.0
END DESCRIPTION:
XS GIS Cut Line= 3
      1679666.72      6984406.26      1678849.06      6984679.48
      1678868.63      6985201.52
#Sta/Elev= 30
  4137.9 1708.30  4219.9 1706.61  4231.5 1706.24  4283.7 1704.57  4352.2 1700.91
  4393.2 1699.53  4446.9 1697.76  4631.2 1694.47  4677.4 1694.35  4839.8 1690.43
  4877.8 1689.24  4930.5 1688.77  4941.0 1687.10  4952.4 1683.55  4957.3 1683.11
  4957.8 1682.61  4967.0 1683.11  4984.0 1683.64  5014.1 1686.79  5018.5 1687.07
  5024.3 1688.79  5029.3 1687.62  5038.5 1689.83  5058.6 1691.05  5112.2 1691.70
  5268.7 1693.98  5328.7 1698.03  5378.8 1699.83  5446.5 1705.44  5522.4 1708.43
#Mann=10,-1,0
  4137.9    0.07       0  4219.9   0.035       0  4231.5    0.07       0
  4393.2   0.035       0  4839.8    0.07       0  4957.3    0.07       0
  4967.0    0.07       0  5014.1   0.035       0  5112.2    0.07       0
  5446.5   0.035       0
Bank Sta=4957.3,4967
Exp/Cntr=0.3,0.1

Type RM Length L Ch R = 1,62029,184,184,184
BEGIN DESCRIPTION:
Mapping XS 36b24340
END DESCRIPTION:
XS GIS Cut Line= 5
      1677299.46      6984214.37      1678080.70      6984801.17
      1678427.92      6985051.17      1678511.25      6985085.89
      1678951.10      6985290.23
#Sta/Elev= 30
  3507.4 1735.52  4271.0 1694.66  4364.8 1688.03  4385.6 1685.14  4391.8 1679.98
  4425.4 1679.60  4535.9 1679.92  4542.1 1681.88  4550.6 1689.17  4571.5 1684.57
  4577.7 1680.72  4592.4 1680.06  4678.3 1680.16  4686.9 1687.03  4693.0 1686.73
  4699.3 1681.72  4707.8 1679.20  4713.9 1681.28  4728.6 1679.25  4985.0 1679.13
  4985.5 1678.63  5000.6 1679.13  5048.4 1679.60  5090.1 1682.29  5118.5 1693.64
  5164.3 1696.17  5190.1 1700.71  5307.1 1707.65  5476.3 1711.31  5487.6 1711.94
#Mann=7,-1,0
  3507.4   0.035       0  4425.4   0.033       0  4985.0   0.033       0
  5000.6   0.033       0  5048.4   0.035       0  5190.1    0.07       0
  5476.3   0.035       0
Bank Sta=4985,5000.6
Exp/Cntr=0.3,0.1

Type RM Length L Ch R = 1,61845,168,168,168
BEGIN DESCRIPTION:
Mapping XS c5c66d9c
END DESCRIPTION:
XS GIS Cut Line= 4
      1677302.89      6984440.04      1677868.89      6984822.00
      1678365.42      6985186.59      1678917.47      6985519.90
#Sta/Elev= 30
  3707.7 1729.32  3765.6 1726.96  3858.5 1716.49  4004.6 1710.84  4121.9 1704.91
  4197.0 1700.41  4197.5 1699.91  4212.8 1700.41  4218.3 1701.27  4371.1 1706.11
  4663.7 1707.23  4678.3 1705.36  4699.2 1707.45  4728.5 1705.39  4764.0 1707.54
  4778.7 1705.09  4799.5 1707.70  4814.2 1704.90  4820.4 1707.16  4828.8 1705.39
  4849.7 1707.89  4864.3 1704.60  4904.8 1706.94  4985.3 1706.89  5003.2 1706.86
  5268.9 1700.81  5410.9 1707.54  5540.7 1711.79  5582.1 1712.51  5651.4 1713.87
#Mann=13,-1,0
  3707.7    0.07       0  4004.6   0.035       0  4121.9    0.07       0
  4197.0   0.035       0  4212.8    0.07       0  4218.3   0.035       0
  4904.8    0.07       0  4985.3   0.035       0  5003.2    0.07       0
  5268.9   0.035       0  5410.9    0.07       0  5540.7   0.035       0
  5582.1    0.07       0
Bank Sta=4197,4212.8
Exp/Cntr=0.3,0.1

Type RM Length L Ch R = 1,61677,878,878,878
BEGIN DESCRIPTION:
Mapping XS aac55812
END DESCRIPTION:
XS GIS Cut Line= 5
      1677153.63      6984585.90      1677518.20      6984818.53
      1677868.89      6985006.03      1678223.06      6985269.92
      1678789.00      6985801.14
#Sta/Elev= 30
  3728.3 1727.38  3781.0 1723.63  3796.2 1720.41  3838.5 1716.34  3958.9 1709.40
  4035.7 1705.46  4041.6 1703.71  4056.8 1704.67  4078.0 1702.59  4188.6 1701.07
  4260.0 1698.19  4276.2 1699.24  4299.8 1695.85  4310.5 1695.01  4424.2 1690.14
  4555.2 1686.37  4765.1 1686.39  4902.6 1683.54  4936.1 1682.94  4949.1 1680.35
  4949.6 1679.85  4964.9 1680.35  4965.1 1682.02  4992.4 1683.08  5035.4 1689.56
  5060.5 1690.18  5325.6 1698.84  5530.7 1702.17  5615.7 1705.46  5776.3 1708.45
#Mann=10,-1,0
  3728.3    0.07       0  3958.9   0.035       0  4188.6    0.07       0
  4299.8   0.035       0  4310.5    0.07       0  4424.2   0.035       0
  4902.6    0.07       0  4949.1    0.07       0  4964.9    0.07       0
  5060.5   0.035       0
Bank Sta=4949.1,4964.9
Exp/Cntr=0.3,0.1

Type RM Length L Ch R = 1,60799,537,537,537
BEGIN DESCRIPTION:
Mapping XS a516750e
END DESCRIPTION:
XS GIS Cut Line= 3
      1676551.03      6985603.02      1677498.99      6985641.21
      1678794.11      6985981.49
#Sta/Elev= 30
  4046.0 1753.05  4110.0 1746.66  4180.1 1745.64  4203.3 1741.23  4240.1 1736.24
  4356.6 1728.19  4400.4 1726.01  4500.3 1721.74  4590.4 1715.20  4705.0 1712.17
  4818.1 1706.71  4930.7 1700.03  4970.7 1688.97  4990.2 1679.96  4994.7 1679.96
  4998.8 1676.92  5013.6 1672.92  5014.1 1672.42  5029.6 1672.92  5036.7 1676.30
  5079.5 1682.05  5299.3 1683.74  5523.8 1684.74  5525.0 1684.75  5530.7 1684.76
  5830.7 1689.05  5906.3 1692.48  6183.6 1698.79  6299.5 1706.59  6333.8 1706.87
#Mann=13,-1,0
  4046.0   0.035       0  4203.3    0.07       0  4356.6   0.035       0
  4400.4    0.07       0  4705.0   0.035       0  4818.1    0.07       0
  5013.6    0.07       0  5029.6    0.07       0  5036.7   0.035       0
  5299.3    0.07       0  5523.8   0.035       0  5525.0    0.07       0
  5530.7   0.035       0
Bank Sta=5013.6,5029.6
Exp/Cntr=0.3,0.1

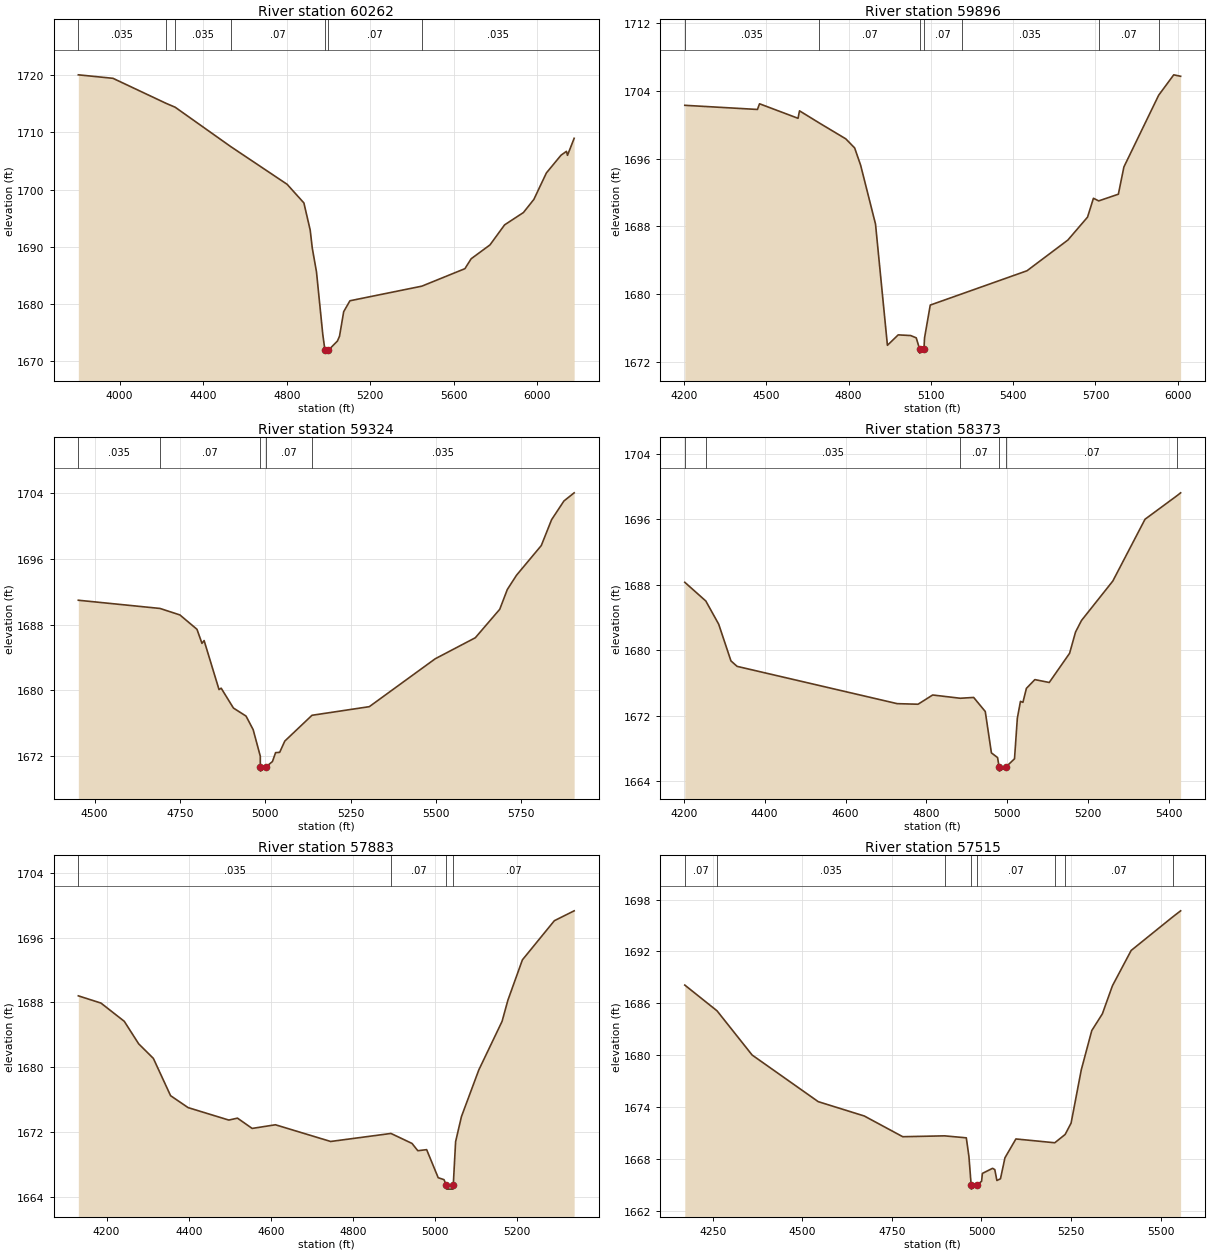
Type RM Length L Ch R = 1,60262,366,366,366
BEGIN DESCRIPTION:
Mapping XS 64c5d829
END DESCRIPTION:
XS GIS Cut Line= 3
      1676519.83      6986207.19      1677710.79      6986092.60
      1678887.89      6986134.27
#Sta/Elev= 30
  3802.0 1720.04  3967.9 1719.43  4223.0 1715.05  4265.5 1714.39  4531.9 1707.51
  4801.8 1700.93  4882.1 1697.68  4912.3 1692.94  4922.3 1689.79  4942.4 1685.65
  4972.6 1674.72  4983.0 1671.96  4983.5 1671.46  4999.0 1671.96  5042.7 1673.57
  5052.7 1674.41  5072.7 1678.70  5102.7 1680.60  5447.0 1683.15  5653.1 1686.20
  5683.1 1687.93  5773.2 1690.35  5843.2 1693.85  5933.3 1696.00  5983.3 1698.29
  6043.3 1702.91  6113.4 1706.01  6139.4 1706.68  6144.4 1705.99  6176.3 1708.96
#Mann=7,-1,0
  3802.0   0.035       0  4223.0    0.07       0  4265.5   0.035       0
  4531.9    0.07       0  4983.0    0.07       0  4999.0    0.07       0
  5447.0   0.035       0
Bank Sta=4983,4999
Exp/Cntr=0.3,0.1

Type RM Length L Ch R = 1,59896,572,572,572
BEGIN DESCRIPTION:
Mapping XS 5db4fde5
END DESCRIPTION:
XS GIS Cut Line= 3
      1677173.78      6986694.72      1677909.85      6986385.70
      1678909.84      6986246.82
#Sta/Elev= 30
  4202.5 1702.27  4467.4 1701.78  4475.0 1702.45  4615.4 1700.74  4620.8 1701.62
  4693.3 1700.18  4789.5 1698.32  4821.8 1697.25  4843.7 1695.21  4897.9 1688.28
  4941.3 1674.00  4980.6 1675.23  5026.2 1675.15  5046.4 1674.88  5058.5 1673.58
  5059.0 1673.08  5074.6 1673.58  5076.7 1674.88  5097.5 1678.74  5213.7 1680.07
  5450.2 1682.78  5599.3 1686.40  5671.0 1689.10  5692.5 1691.32  5711.7 1691.01
  5783.4 1691.80  5803.6 1695.01  5930.4 1703.46  5985.3 1705.86  6010.4 1705.69
#Mann=7,-1,0
  4202.5   0.035       0  4693.3    0.07       0  5058.5    0.07       0
  5074.6    0.07       0  5213.7   0.035       0  5711.7    0.07       0
  5930.4   0.035       0
Bank Sta=5058.5,5074.6
Exp/Cntr=0.3,0.1

Type RM Length L Ch R = 1,59324,951,951,951
BEGIN DESCRIPTION:
Mapping XS 378cecc6
END DESCRIPTION:
XS GIS Cut Line= 3
      1677741.46      6987191.25      1678178.95      6986863.13
      1678937.60      6986368.36
#Sta/Elev= 30
  4452.3 1690.97  4691.6 1689.97  4749.9 1689.18  4799.9 1687.43  4814.5 1685.72
  4820.8 1686.06  4864.5 1680.09  4870.8 1680.26  4906.7 1677.84  4943.7 1676.86
  4964.5 1675.21  4985.4 1671.98  4985.5 1670.66  4986.0 1670.16  5001.6 1670.66
  5021.0 1671.33  5030.2 1672.41  5042.2 1672.45  5057.2 1673.82  5136.9 1676.96
  5304.8 1678.01  5497.8 1683.84  5615.3 1686.40  5686.9 1689.87  5709.1 1692.28
  5736.1 1694.02  5808.6 1697.63  5838.8 1700.78  5875.0 1703.06  5904.9 1704.05
#Mann=5,-1,0
  4452.3   0.035       0  4691.6    0.07       0  4985.5    0.07       0
  5001.6    0.07       0  5136.9   0.035       0
Bank Sta=4985.5,5001.6
Exp/Cntr=0.3,0.1

Type RM Length L Ch R = 1,58373,490,490,490
BEGIN DESCRIPTION:
Mapping XS aa6765fe
END DESCRIPTION:
XS GIS Cut Line= 3
      1677985.10      6987100.44      1678654.34      6987532.71
      1679002.62      6987783.52
#Sta/Elev= 30
  4202.6 1688.30  4254.6 1686.01  4286.4 1683.18  4316.7 1678.69  4331.9 1678.02
  4727.8 1673.46  4779.3 1673.39  4815.5 1674.52  4883.7 1674.12  4916.8 1674.22
  4945.5 1672.50  4960.7 1667.44  4975.9 1666.87  4979.8 1665.71  4980.3 1665.21
  4996.5 1665.71  5017.8 1666.72  5024.8 1671.68  5032.5 1673.74  5038.6 1673.62
  5047.2 1675.33  5068.1 1676.40  5103.7 1676.05  5154.0 1679.62  5168.7 1682.22
  5183.4 1683.63  5260.8 1688.45  5340.5 1696.01  5420.1 1698.91  5428.5 1699.24
#Mann=6,-1,0
  4202.6    0.07       0  4254.6   0.035       0  4883.7    0.07       0
  4979.8    0.07       0  4996.5    0.07       0  5420.1   0.035       0
Bank Sta=4979.8,4996.5
Exp/Cntr=0.3,0.1

Type RM Length L Ch R = 1,57883,368,368,368
BEGIN DESCRIPTION:
Mapping XS 806dcebc
END DESCRIPTION:
XS GIS Cut Line= 3
      1677789.67      6987325.59      1678430.29      6987912.40
      1678667.80      6988153.37
#Sta/Elev= 30
  4131.3 1688.82  4186.3 1687.93  4243.1 1685.68  4278.2 1682.90  4314.0 1681.10
  4355.9 1676.50  4398.5 1675.03  4497.7 1673.49  4518.7 1673.73  4554.5 1672.46
  4611.2 1672.91  4745.6 1670.85  4892.4 1671.84  4943.6 1670.61  4957.8 1669.71
  4979.3 1669.84  5007.4 1666.38  5021.5 1666.14  5027.3 1665.47  5027.8 1664.97
  5043.6 1664.97  5044.1 1665.47  5049.8 1670.83  5064.0 1673.92  5106.3 1679.68
  5162.9 1685.67  5177.0 1688.27  5212.4 1693.26  5290.2 1698.09  5338.4 1699.31
#Mann=4,-1,0
  4131.3   0.035       0  4892.4    0.07       0  5027.3    0.07       0
  5044.1    0.07       0
Bank Sta=5027.3,5044.1
Exp/Cntr=0.3,0.1

Type RM Length L Ch R = 1,57515,528,528,528
BEGIN DESCRIPTION:
Mapping XS 3a553bf0
END DESCRIPTION:
XS GIS Cut Line= 3
      1677454.58      6987525.22      1678110.85      6988035.66
      1678590.02      6988311.70
#Sta/Elev= 30
  4171.6 1688.11  4261.6 1685.13  4359.6 1680.01  4544.2 1674.61  4672.7 1672.95
  4780.2 1670.55  4896.9 1670.65  4957.6 1670.42  4965.0 1668.24  4971.1 1664.98
  4971.6 1664.48  4987.9 1664.98  5000.3 1665.39  5002.5 1666.30  5030.9 1666.89
  5037.2 1666.74  5043.0 1665.48  5053.0 1665.68  5065.5 1668.11  5096.1 1670.29
  5204.6 1669.85  5233.6 1670.81  5250.2 1672.13  5278.6 1678.29  5307.9 1682.84
  5337.5 1684.78  5365.6 1688.03  5417.9 1692.12  5533.8 1696.00  5556.0 1696.71
#Mann=8,-1,0
  4171.6    0.07       0  4261.6   0.035       0  4896.9    0.07       0
  4971.1    0.07       0  4987.9    0.07       0  5204.6   0.035       0
  5233.6    0.07       0  5533.8   0.035       0
Bank Sta=4971.1,4987.9
Exp/Cntr=0.3,0.1

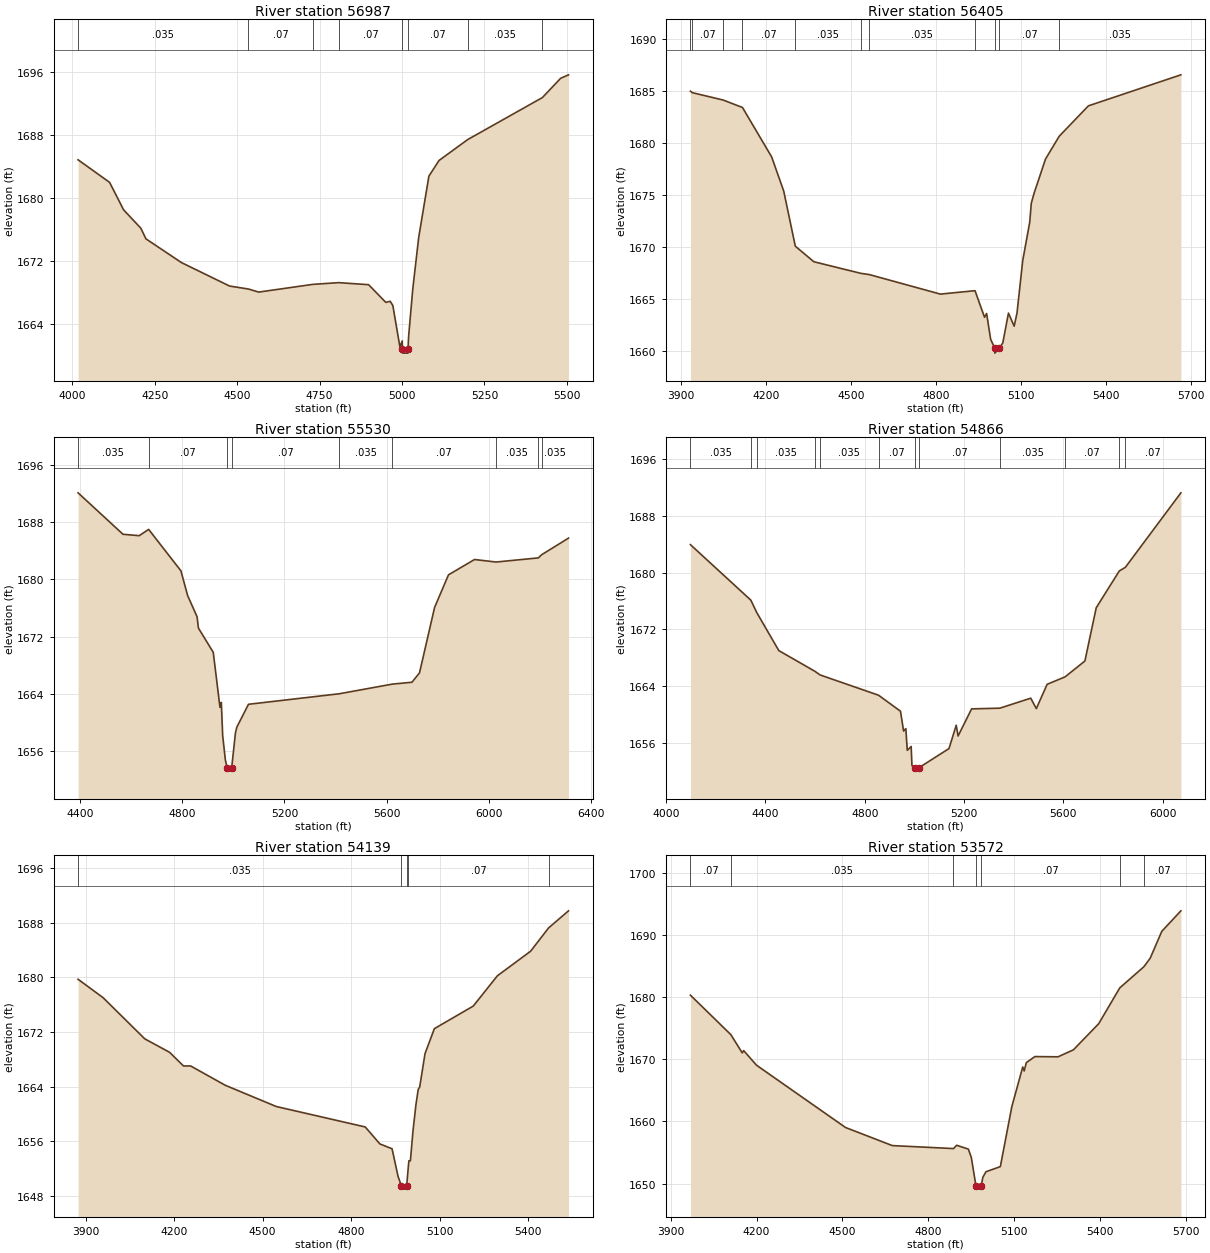
Type RM Length L Ch R = 1,56987,582,582,582
BEGIN DESCRIPTION:
Mapping XS 20154408
END DESCRIPTION:
XS GIS Cut Line= 3
      1677257.58      6987983.68      1678096.16      6988496.73
      1678588.38      6988606.11
#Sta/Elev= 30
  4017.6 1684.83  4113.2 1681.96  4155.8 1678.46  4208.0 1676.13  4223.4 1674.78
  4331.1 1671.76  4476.9 1668.78  4534.2 1668.40  4565.6 1668.01  4729.4 1668.99
  4808.1 1669.21  4898.7 1668.95  4950.9 1666.70  4964.1 1666.84  4972.2 1666.30
  4993.5 1661.06  5000.7 1661.80  5001.3 1660.75  5001.8 1660.25  5017.6 1660.25
  5018.1 1660.75  5020.0 1662.37  5032.5 1668.37  5050.7 1674.99  5081.4 1682.74
  5112.2 1684.74  5198.8 1687.39  5425.7 1692.74  5481.0 1695.19  5504.9 1695.63
#Mann=8,-1,0
  4017.6   0.035       0  4534.2    0.07       0  4729.4   0.035       0
  4808.1    0.07       0  5001.3    0.07       0  5018.1    0.07       0
  5198.8   0.035       0  5425.7    0.07       0
Bank Sta=5001.3,5018.1
Exp/Cntr=0.3,0.1

Type RM Length L Ch R = 1,56405,875,875,875
BEGIN DESCRIPTION:
Mapping XS 0d18b7ee
END DESCRIPTION:
XS GIS Cut Line= 3
      1677067.50      6988171.19      1677783.66      6988965.48
      1678439.86      6988900.38
#Sta/Elev= 30
  3934.6 1685.00  3941.2 1684.86  4049.9 1684.15  4118.1 1683.43  4220.9 1678.67
  4263.5 1675.37  4304.3 1670.06  4369.7 1668.56  4535.7 1667.44  4565.5 1667.32
  4815.8 1665.44  4937.8 1665.77  4971.3 1663.21  4978.7 1663.57  4992.9 1661.08
  5007.0 1660.25  5007.5 1659.75  5023.9 1660.25  5035.6 1660.72  5055.7 1663.61
  5075.8 1662.35  5085.8 1663.61  5105.9 1668.66  5130.7 1672.38  5136.1 1674.19
  5146.1 1675.17  5186.3 1678.46  5234.6 1680.66  5337.5 1683.59  5663.5 1686.58
#Mann=11,-1,0
  3934.6   0.035       0  3941.2    0.07       0  4049.9   0.035       0
  4118.1    0.07       0  4304.3   0.035       0  4535.7    0.07       0
  4565.5   0.035       0  4937.8    0.07       0  5007.0    0.07       0
  5023.9    0.07       0  5234.6   0.035       0
Bank Sta=5007,5023.9
Exp/Cntr=0.3,0.1

Type RM Length L Ch R = 1,55530,664,664,664
BEGIN DESCRIPTION:
Mapping XS 2e6f06a5
END DESCRIPTION:
XS GIS Cut Line= 3
      1676708.15      6989710.26      1677278.45      6989520.16
      1678467.99      6988952.72
#Sta/Elev= 30
  4392.6 1692.10  4568.4 1686.31  4631.7 1686.11  4668.8 1686.99  4795.1 1681.20
  4821.4 1677.74  4858.3 1674.78  4863.6 1673.20  4921.6 1669.81  4947.9 1662.12
  4953.2 1662.81  4958.5 1658.16  4969.0 1654.76  4975.9 1653.71  4976.4 1653.21
  4993.8 1653.71  5008.5 1658.58  5014.0 1659.37  5059.4 1662.55  5414.7 1664.02
  5622.5 1665.37  5699.0 1665.63  5728.6 1666.94  5787.7 1676.09  5842.0 1680.64
  5943.9 1682.78  6028.3 1682.43  6193.8 1683.01  6206.1 1683.44  6311.7 1685.77
#Mann=9,-1,0
  4392.6   0.035       0  4668.8    0.07       0  4975.9    0.07       0
  4993.8    0.07       0  5414.7   0.035       0  5622.5    0.07       0
  6028.3   0.035       0  6193.8    0.07       0  6206.1   0.035       0
Bank Sta=4975.9,4993.8
Exp/Cntr=0.3,0.1

Type RM Length L Ch R = 1,54866,727,727,727
BEGIN DESCRIPTION:
Mapping XS 29724cef
END DESCRIPTION:
XS GIS Cut Line= 3
      1677015.22      6990294.75      1677785.61      6989841.20
      1678780.83      6989418.39
#Sta/Elev= 30
  4097.8 1683.96  4341.0 1676.13  4365.5 1674.34  4453.8 1669.00  4598.6 1666.09
  4620.2 1665.56  4855.4 1662.70  4943.8 1660.44  4956.3 1657.64  4965.3 1657.98
  4971.1 1654.92  4986.8 1655.46  4990.0 1652.75  5001.1 1652.48  5001.6 1651.98
  5019.1 1652.48  5139.2 1655.17  5168.3 1658.46  5175.8 1656.94  5230.2 1660.77
  5343.9 1660.87  5468.4 1662.28  5490.9 1660.81  5534.4 1664.24  5606.7 1665.29
  5686.5 1667.53  5732.1 1675.05  5825.1 1680.25  5849.5 1680.76  6073.1 1691.28
#Mann=12,-1,0
  4097.8   0.035       0  4341.0    0.07       0  4365.5   0.035       0
  4598.6    0.07       0  4620.2   0.035       0  4855.4    0.07       0
  5001.1    0.07       0  5019.1    0.07       0  5343.9   0.035       0
  5606.7    0.07       0  5825.1   0.035       0  5849.5    0.07       0
Bank Sta=5001.1,5019.1
Exp/Cntr=0.3,0.1

Type RM Length L Ch R = 1,54139,567,567,567
BEGIN DESCRIPTION:
Mapping XS e2f6a9b7
END DESCRIPTION:
XS GIS Cut Line= 3
      1677091.07      6990435.96      1678203.00      6990279.71
      1678730.83      6990167.91
#Sta/Elev= 30
  3874.7 1679.74  3959.5 1677.04  4100.8 1671.00  4185.0 1669.02  4232.1 1667.02
  4256.3 1667.02  4373.5 1664.19  4546.5 1661.07  4848.1 1658.07  4897.8 1655.58
  4939.0 1654.87  4959.2 1650.84  4970.3 1649.45  4970.8 1648.95  4988.0 1648.95
  4988.5 1649.45  4993.9 1652.13  4996.0 1653.10  5001.1 1653.10  5009.8 1657.44
  5020.0 1661.37  5027.6 1663.56  5032.7 1663.94  5050.7 1668.83  5082.3 1672.49
  5214.3 1675.81  5296.0 1680.25  5408.5 1683.85  5469.5 1687.27  5537.1 1689.78
#Mann=5,-1,0
  3874.7   0.035       0  4970.3    0.07       0  4988.5   0.035       0
  4993.9    0.07       0  5469.5   0.035       0
Bank Sta=4970.3,4988.5
Exp/Cntr=0.3,0.1

Type RM Length L Ch R = 1,53572,494,494,494
BEGIN DESCRIPTION:
Mapping XS e92f4b42
END DESCRIPTION:
XS GIS Cut Line= 3
      1677195.10      6991010.79      1678198.57      6990798.98
      1678881.35      6990719.27
#Sta/Elev= 30
  3969.2 1680.28  4110.7 1673.92  4150.1 1671.00  4155.2 1671.37  4199.8 1669.03
  4510.8 1659.01  4674.3 1656.10  4887.9 1655.62  4899.2 1656.15  4940.0 1655.53
  4950.3 1654.18  4966.5 1649.60  4967.0 1649.10  4984.7 1649.60  4990.4 1650.99
  5001.3 1651.89  5051.6 1652.72  5091.9 1662.39  5129.9 1668.74  5134.9 1668.10
  5142.2 1669.43  5172.4 1670.41  5253.0 1670.37  5306.7 1671.49  5395.1 1675.69
  5468.9 1681.46  5552.9 1684.85  5575.1 1686.23  5615.4 1690.54  5682.2 1693.84
#Mann=7,-1,0
  3969.2    0.07       0  4110.7   0.035       0  4887.9    0.07       0
  4966.5    0.07       0  4984.7    0.07       0  5468.9   0.035       0
  5552.9    0.07       0
Bank Sta=4966.5,4984.7
Exp/Cntr=0.3,0.1

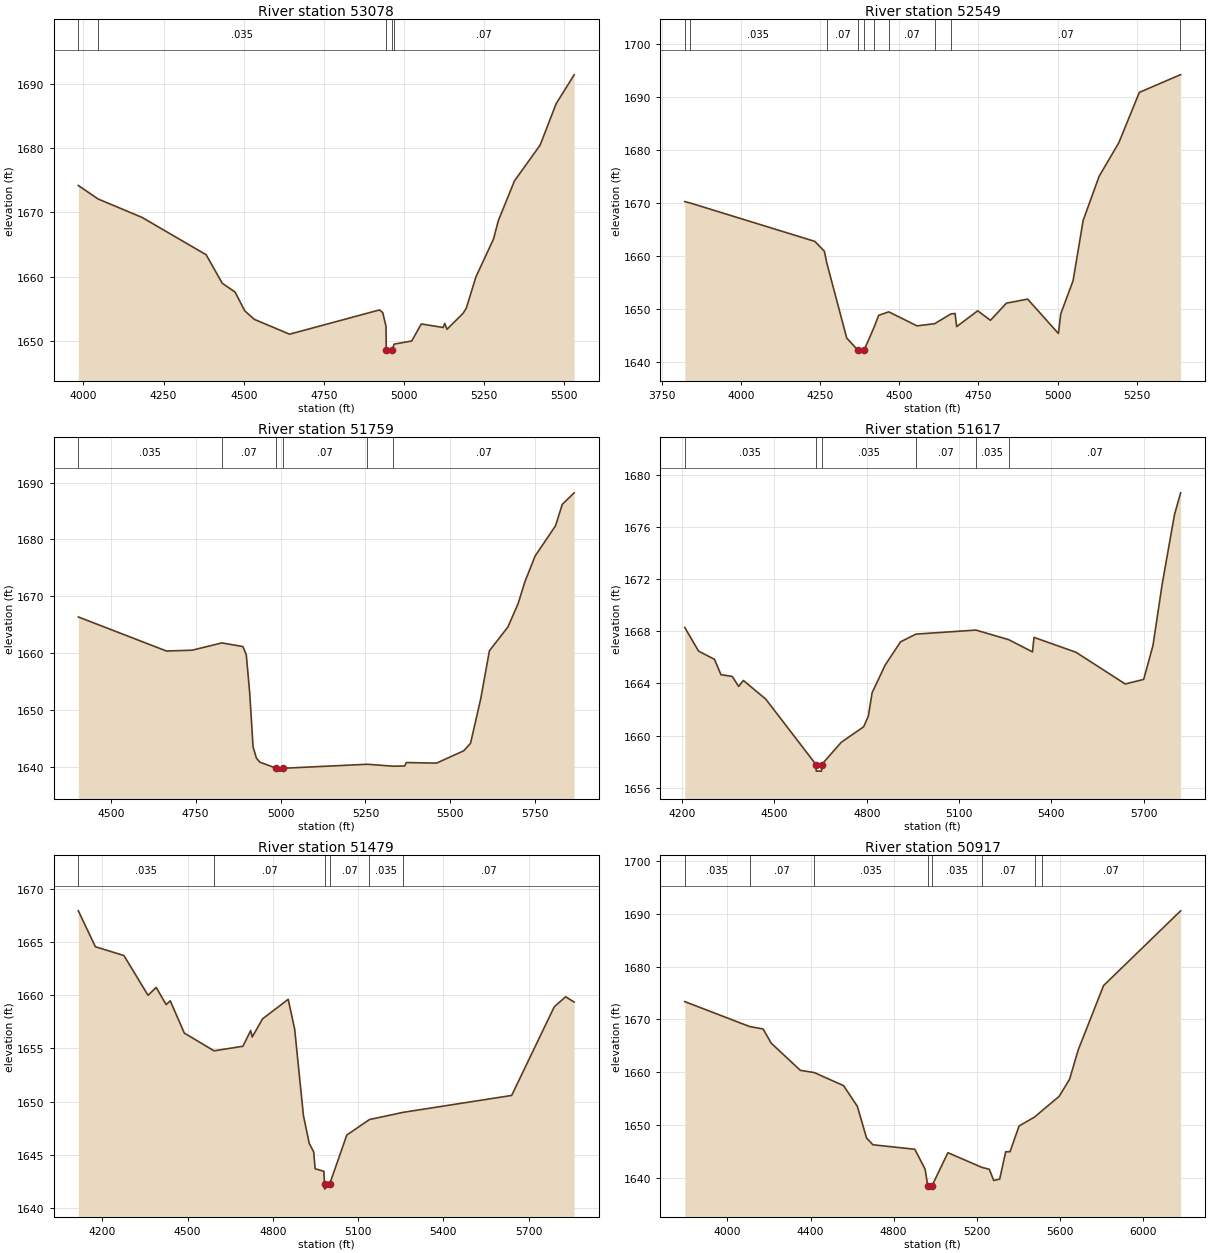
Type RM Length L Ch R = 1,53078,529,529,529
BEGIN DESCRIPTION:
Mapping XS 184ecdb8
END DESCRIPTION:
XS GIS Cut Line= 3
      1677196.73      6991354.25      1678207.98      6991291.31
      1678740.95      6991256.65
#Sta/Elev= 30
  3983.9 1674.17  4045.5 1672.08  4182.6 1669.22  4382.9 1663.42  4433.0 1659.00
  4473.1 1657.63  4503.2 1654.72  4533.2 1653.39  4643.2 1651.09  4924.0 1654.86
  4934.0 1654.42  4944.0 1652.31  4944.9 1648.65  4945.4 1648.15  4963.2 1648.65
  4969.3 1649.55  5024.2 1650.03  5054.2 1652.68  5122.3 1652.13  5127.3 1652.77
  5134.4 1651.85  5184.5 1654.33  5194.5 1655.11  5224.6 1659.98  5279.5 1665.86
  5294.8 1668.75  5344.9 1674.88  5425.0 1680.44  5475.1 1686.88  5531.2 1691.35
#Mann=5,-1,0
  3983.9    0.07       0  4045.5   0.035       0  4944.9    0.07       0
  4963.2   0.035       0  4969.3    0.07       0
Bank Sta=4944.9,4963.2
Exp/Cntr=0.3,0.1

Type RM Length L Ch R = 1,52549,790,790,790
BEGIN DESCRIPTION:
Mapping XS b0fe2e41
END DESCRIPTION:
XS GIS Cut Line= 3
      1677188.00      6991519.18      1678355.55      6991675.43
      1678739.67      6991731.85
#Sta/Elev= 30
  3822.4 1670.27  3838.1 1670.03  4233.1 1662.77  4263.3 1660.92  4270.9 1658.72
  4333.9 1644.55  4370.0 1642.21  4370.5 1641.71  4388.3 1642.21  4419.5 1646.47
  4434.8 1648.84  4466.6 1649.49  4555.9 1646.85  4611.8 1647.26  4663.0 1649.10
  4676.2 1649.18  4681.2 1646.71  4747.6 1649.69  4787.9 1647.90  4838.4 1651.13
  4905.3 1651.89  5002.6 1645.41  5009.9 1649.11  5048.9 1655.36  5080.7 1666.72
  5131.2 1675.04  5193.5 1681.38  5258.2 1690.85  5387.2 1694.16  5388.6 1694.16
#Mann=10,-1,0
  3822.4    0.07       0  3838.1   0.035       0  4270.9    0.07       0
  4370.0    0.07       0  4388.3    0.07       0  4419.5   0.035       0
  4466.6    0.07       0  4611.8   0.035       0  4663.0    0.07       0
  5387.2   0.035       0
Bank Sta=4370,4388.3
Exp/Cntr=0.3,0.1

Type RM Length L Ch R = 1,51759,142,142,142
BEGIN DESCRIPTION:
Fish Creek 85.0
END DESCRIPTION:
XS GIS Cut Line= 4
      1677170.85      6991729.00      1677532.82      6991926.91
      1677715.77      6991928.27      1678579.97      6991963.00
#Sta/Elev= 30
  4404.5 1666.34  4664.3 1660.34  4739.8 1660.49  4827.2 1661.77  4889.2 1661.13
  4899.2 1659.69  4909.2 1653.03  4919.2 1643.45  4929.2 1641.47  4939.2 1640.78
  4988.0 1639.70  4988.5 1639.20  5005.8 1639.20  5006.3 1639.70  5256.2 1640.41
  5330.9 1640.07  5365.7 1640.10  5370.7 1640.71  5459.6 1640.61  5539.7 1642.78
  5559.7 1644.10  5589.7 1651.93  5615.3 1660.38  5669.8 1664.58  5699.8 1668.68
  5719.8 1672.53  5749.8 1677.06  5809.9 1682.38  5829.9 1686.16  5864.9 1688.19
#Mann=6,-1,0
  4404.5   0.035       0  4827.2    0.07       0  4988.0    0.07       0
  5006.3    0.07       0  5256.2   0.035       0  5330.9    0.07       0
Bank Sta=4988,5006.3
Exp/Cntr=0.3,0.1

Type RM Length L Ch R = 1,51617,138,138,138
BEGIN DESCRIPTION:
Mapping XS 1f18fc05
END DESCRIPTION:
XS GIS Cut Line= 4
      1677012.01      6991729.01      1677538.03      6992064.93
      1677702.09      6992067.54      1678524.97      6992080.56
#Sta/Elev= 30
  4208.9 1668.28  4253.7 1666.47  4305.3 1665.84  4326.5 1664.66  4362.9 1664.53
  4384.0 1663.76  4399.2 1664.22  4472.0 1662.79  4635.4 1657.77  4635.9 1657.27
  4653.2 1657.27  4653.7 1657.77  4717.3 1659.48  4790.1 1660.67  4805.3 1661.48
  4817.6 1663.28  4860.0 1665.40  4910.0 1667.18  4959.7 1667.77  5155.1 1668.08
  5261.1 1667.35  5338.7 1666.41  5343.7 1667.52  5480.1 1666.38  5640.1 1663.95
  5700.1 1664.30  5730.1 1666.88  5760.1 1671.59  5800.1 1676.92  5820.1 1678.60
#Mann=6,-1,0
  4208.9   0.035       0  4635.4    0.07       0  4653.7   0.035       0
  4959.7    0.07       0  5155.1   0.035       0  5261.1    0.07       0
Bank Sta=4635.4,4653.7
Exp/Cntr=0.3,0.1

Type RM Length L Ch R = 1,51479,562,562,562
BEGIN DESCRIPTION:
Fish Creek 84.0
END DESCRIPTION:
XS GIS Cut Line= 4
      1676959.88      6991768.05      1677410.21      6992136.16
      1677705.01      6992205.99      1678564.89      6992186.46
#Sta/Elev= 30
  4115.4 1667.96  4175.4 1664.58  4275.9 1663.75  4360.6 1660.01  4389.3 1660.75
  4424.5 1659.13  4438.8 1659.49  4488.4 1656.45  4593.1 1654.78  4694.4 1655.21
  4722.0 1656.69  4727.2 1656.08  4763.6 1657.79  4853.9 1659.63  4876.7 1656.81
  4907.5 1648.69  4928.0 1646.06  4943.5 1645.27  4948.7 1643.68  4979.4 1643.44
  4981.8 1642.26  4982.3 1641.76  5000.1 1642.26  5060.0 1646.85  5139.7 1648.31
  5258.5 1648.99  5640.2 1650.58  5790.2 1658.93  5830.2 1659.87  5860.1 1659.37
#Mann=6,-1,0
  4115.4   0.035       0  4593.1    0.07       0  4981.8    0.07       0
  5000.1    0.07       0  5139.7   0.035       0  5258.5    0.07       0
Bank Sta=4981.8,5000.1
Exp/Cntr=0.3,0.1

Type RM Length L Ch R = 1,50917,798,798,798
BEGIN DESCRIPTION:
Fish Creek 83.0
END DESCRIPTION:
XS GIS Cut Line= 3
      1676530.90      6992181.86      1677605.00      6992738.00
      1678537.85      6993456.16
#Sta/Elev= 30
  3794.6 1673.37  4107.2 1668.64  4171.6 1668.19  4210.3 1665.51  4351.0 1660.35
  4418.0 1659.93  4558.8 1657.46  4625.2 1653.54  4669.5 1647.55  4700.1 1646.26
  4901.7 1645.41  4951.6 1641.63  4964.4 1638.36  4964.9 1637.86  4983.0 1638.36
  5061.2 1644.76  5223.9 1641.99  5260.5 1641.62  5281.8 1639.49  5310.4 1639.76
  5339.4 1644.95  5360.2 1644.94  5403.7 1649.82  5478.2 1651.51  5513.3 1652.68
  5596.7 1655.43  5646.6 1658.65  5688.2 1664.19  5810.5 1676.41  6181.4 1690.56
#Mann=8,-1,0
  3794.6   0.035       0  4107.2    0.07       0  4418.0   0.035       0
  4964.4   0.035       0  4983.0   0.035       0  5223.9    0.07       0
  5478.2   0.035       0  5513.3    0.07       0
Bank Sta=4964.4,4983
Exp/Cntr=0.3,0.1

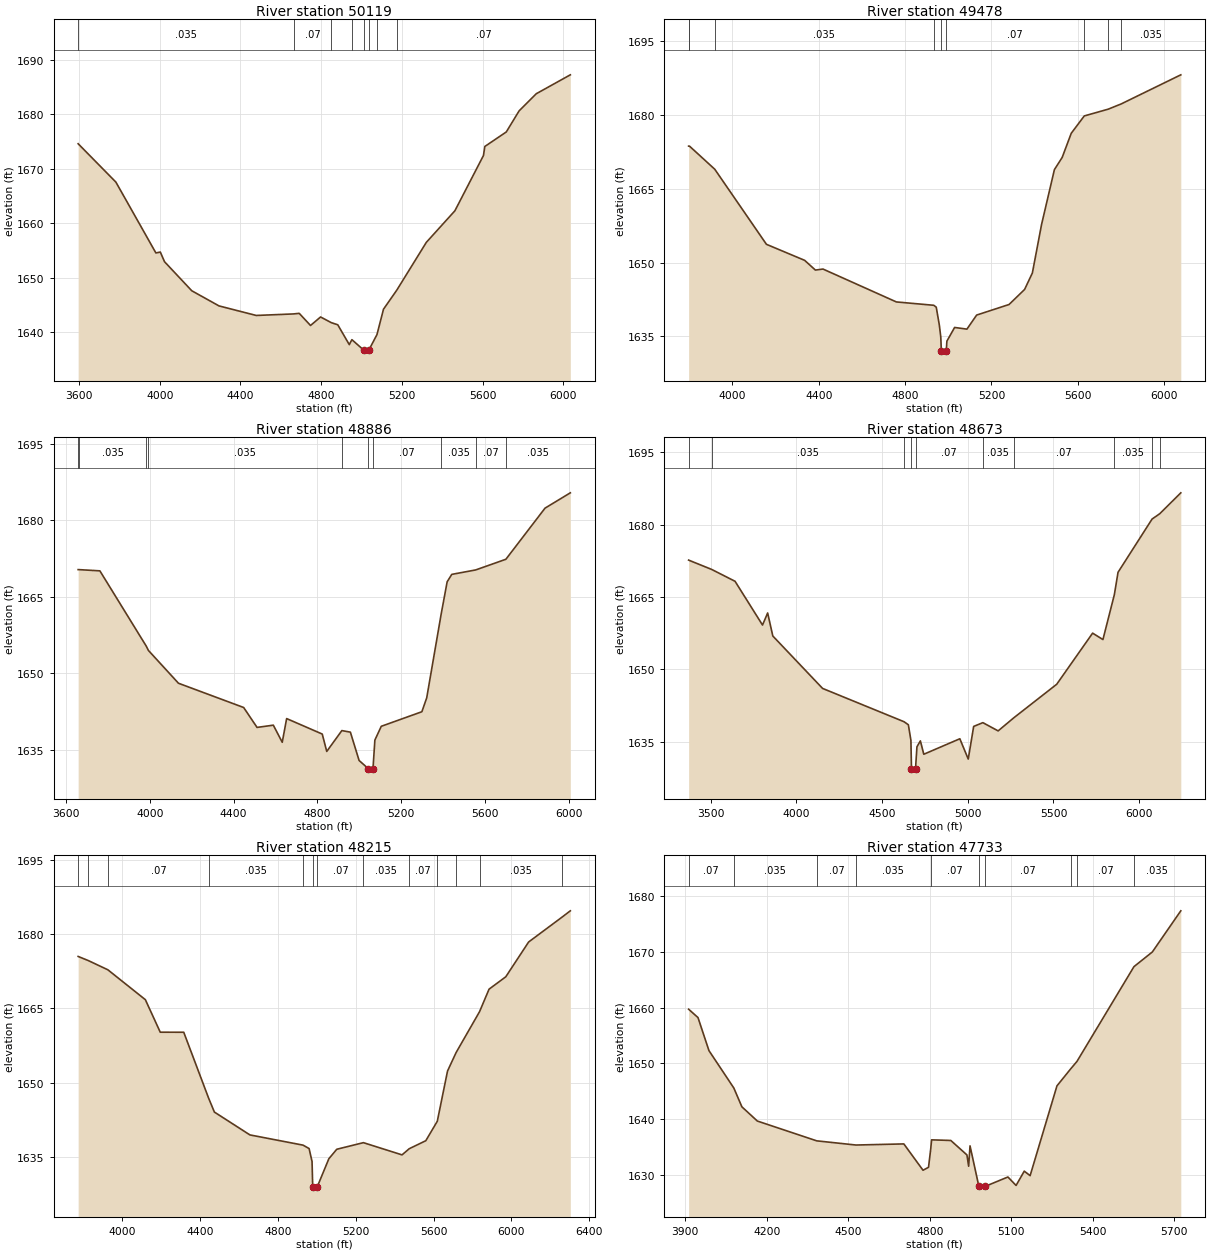
Type RM Length L Ch R = 1,50119,641,641,641
BEGIN DESCRIPTION:
Mapping XS 32bc9a23
END DESCRIPTION:
XS GIS Cut Line= 3
      1676393.04      6992526.28      1677462.52      6993442.98
      1678201.04      6994160.69
#Sta/Elev= 30
  3595.7 1674.57  3782.7 1667.53  3980.8 1654.54  4002.8 1654.70  4023.6 1652.93
  4158.6 1647.60  4293.6 1644.82  4478.0 1643.07  4662.6 1643.35  4690.9 1643.46
  4746.9 1641.23  4796.8 1642.79  4849.9 1641.75  4881.9 1641.36  4939.0 1637.72
  4951.9 1638.63  5012.3 1636.66  5012.8 1636.16  5035.0 1636.66  5076.1 1639.56
  5108.5 1644.22  5174.3 1647.71  5320.7 1656.48  5462.2 1662.27  5603.7 1672.41
  5610.6 1674.07  5716.8 1676.73  5780.4 1680.60  5865.3 1683.74  6034.1 1687.21
#Mann=8,-1,0
  3595.7   0.035       0  4662.6    0.07       0  4849.9   0.035       0
  4951.9    0.07       0  5012.3    0.07       0  5035.0    0.07       0
  5076.1   0.035       0  5174.3    0.07       0
Bank Sta=5012.3,5035
Exp/Cntr=0.3,0.1

Type RM Length L Ch R = 1,49478,592,592,592
BEGIN DESCRIPTION:
Mapping XS 9c40e3fe
END DESCRIPTION:
XS GIS Cut Line= 3
      1676070.16      6992974.23      1676979.88      6993769.37
      1677871.16      6994365.86
#Sta/Elev= 30
  3797.1 1673.71  3801.1 1673.71  3918.2 1669.01  4157.7 1653.74  4334.8 1650.48
  4384.6 1648.50  4419.7 1648.71  4759.8 1642.02  4933.1 1641.34  4944.6 1640.95
  4958.8 1637.33  4965.5 1634.92  4968.2 1632.11  4968.7 1631.61  4991.1 1632.11
  4993.9 1634.05  5029.7 1636.83  5086.7 1636.49  5131.8 1639.35  5281.9 1641.50
  5354.0 1644.56  5390.0 1647.91  5432.6 1657.78  5492.1 1668.93  5528.1 1671.41
  5570.1 1676.32  5630.5 1679.85  5741.1 1681.22  5801.6 1682.29  6077.8 1688.21
#Mann=9,-1,0
  3797.1   0.035       0  3801.1    0.07       0  3918.2   0.035       0
  4933.1    0.07       0  4968.2    0.07       0  4991.1    0.07       0
  5630.5   0.035       0  5741.1    0.07       0  5801.6   0.035       0
Bank Sta=4968.2,4991.1
Exp/Cntr=0.3,0.1

Type RM Length L Ch R = 1,48886,213,213,213
BEGIN DESCRIPTION:
Mapping XS 0d9fb7a2
END DESCRIPTION:
XS GIS Cut Line= 3
      1675880.35      6993315.90      1676803.96      6994291.59
      1677790.06      6994486.03
#Sta/Elev= 30
  3658.5 1670.31  3662.0 1670.31  3762.2 1670.07  3983.0 1655.36  3993.7 1654.49
  4137.2 1648.06  4448.3 1643.31  4512.2 1639.41  4589.9 1639.85  4632.4 1636.50
  4653.4 1641.14  4823.3 1638.11  4844.8 1634.71  4916.9 1638.79  4957.6 1638.48
  4999.1 1632.94  5042.6 1631.35  5043.1 1630.85  5065.5 1631.35  5074.4 1636.92
  5105.0 1639.63  5298.7 1642.48  5321.8 1645.20  5391.0 1661.66  5419.4 1667.94
  5441.4 1669.38  5555.6 1670.25  5699.6 1672.34  5886.4 1682.35  6007.1 1685.35
#Mann=10,-1,0
  3658.5    0.07       0  3662.0   0.035       0  3983.0    0.07       0
  3993.7   0.035       0  4916.9    0.07       0  5042.6    0.07       0
  5065.5    0.07       0  5391.0   0.035       0  5555.6    0.07       0
  5699.6   0.035       0
Bank Sta=5042.6,5065.5
Exp/Cntr=0.3,0.1

Type RM Length L Ch R = 1,48673,458,458,458
BEGIN DESCRIPTION:
Mapping XS c6af5797
END DESCRIPTION:
XS GIS Cut Line= 3
      1675064.38      6994361.03      1676689.37      6994451.31
      1677910.76      6994694.20
#Sta/Elev= 30
  3370.6 1672.67  3505.0 1670.74  3641.6 1668.28  3801.9 1659.21  3831.9 1661.71
  3862.0 1656.94  4152.4 1646.07  4628.1 1639.16  4653.2 1638.53  4668.1 1635.30
  4671.4 1629.42  4671.9 1628.92  4695.0 1629.42  4703.3 1633.97  4723.3 1635.19
  4743.3 1632.42  4953.7 1635.63  5002.7 1631.42  5034.4 1638.19  5088.1 1638.97
  5177.2 1637.26  5268.4 1639.97  5519.1 1646.93  5728.7 1657.53  5788.9 1656.20
  5855.7 1665.53  5877.0 1670.14  6075.7 1681.18  6120.6 1682.29  6243.4 1686.62
#Mann=10,-1,0
  3370.6    0.07       0  3505.0   0.035       0  4628.1    0.07       0
  4671.4    0.07       0  4695.0    0.07       0  5088.1   0.035       0
  5268.4    0.07       0  5855.7   0.035       0  6075.7    0.07       0
  6120.6   0.035       0
Bank Sta=4671.4,4695
Exp/Cntr=0.3,0.1

Type RM Length L Ch R = 1,48215,482,482,482
BEGIN DESCRIPTION:
Mapping XS 402a487e
END DESCRIPTION:
XS GIS Cut Line= 3
      1675144.28      6994482.57      1676356.04      6994687.42
      1677635.84      6994923.27
#Sta/Elev= 30
  3772.7 1675.48  3824.3 1674.66  3925.6 1672.79  4118.3 1666.77  4194.8 1660.22
  4315.6 1660.21  4444.1 1646.87  4473.2 1644.13  4655.8 1639.53  4929.0 1637.47
  4960.0 1636.78  4975.2 1634.17  4978.6 1629.11  4979.1 1628.61  5002.3 1629.11
  5061.6 1634.73  5102.3 1636.64  5239.2 1637.97  5437.8 1635.51  5474.8 1636.75
  5559.9 1638.36  5619.1 1642.28  5671.7 1652.40  5715.8 1656.12  5836.5 1664.37
  5885.2 1668.89  5971.1 1671.38  6088.6 1678.39  6258.7 1683.35  6303.0 1684.67
#Mann=13,-1,0
  3772.7    0.07       0  3824.3   0.035       0  3925.6    0.07       0
  4444.1   0.035       0  4929.0    0.07       0  4978.6    0.07       0
  5002.3    0.07       0  5239.2   0.035       0  5474.8    0.07       0
  5619.1   0.035       0  5715.8    0.07       0  5836.5   0.035       0
  6258.7    0.07       0
Bank Sta=4978.6,5002.3
Exp/Cntr=0.3,0.1

Type RM Length L Ch R = 1,47733,484,484,484
BEGIN DESCRIPTION:
Mapping XS fc459531
END DESCRIPTION:
XS GIS Cut Line= 3
      1675510.89      6994867.06      1676580.37      6995019.84
      1677309.52      6995075.40
#Sta/Elev= 30
  3912.4 1659.74  3946.9 1658.24  3987.3 1652.30  4078.8 1645.59  4108.5 1642.21
  4165.3 1639.66  4383.9 1636.10  4528.4 1635.35  4704.5 1635.55  4775.2 1630.82
  4795.4 1631.35  4803.8 1634.77  4806.7 1636.28  4877.4 1636.17  4936.8 1633.57
  4943.1 1631.54  4948.2 1635.20  4980.7 1627.93  4981.2 1627.43  5004.4 1627.93
  5087.6 1629.61  5117.7 1628.09  5147.8 1630.66  5169.4 1629.85  5268.2 1645.98
  5320.1 1649.11  5341.7 1650.36  5551.5 1667.38  5619.2 1670.02  5724.0 1677.41
#Mann=10,-1,0
  3912.4    0.07       0  4078.8   0.035       0  4383.9    0.07       0
  4528.4   0.035       0  4803.8    0.07       0  4980.7    0.07       0
  5004.4    0.07       0  5320.1   0.035       0  5341.7    0.07       0
  5551.5   0.035       0
Bank Sta=4980.7,5004.4
Exp/Cntr=0.3,0.1