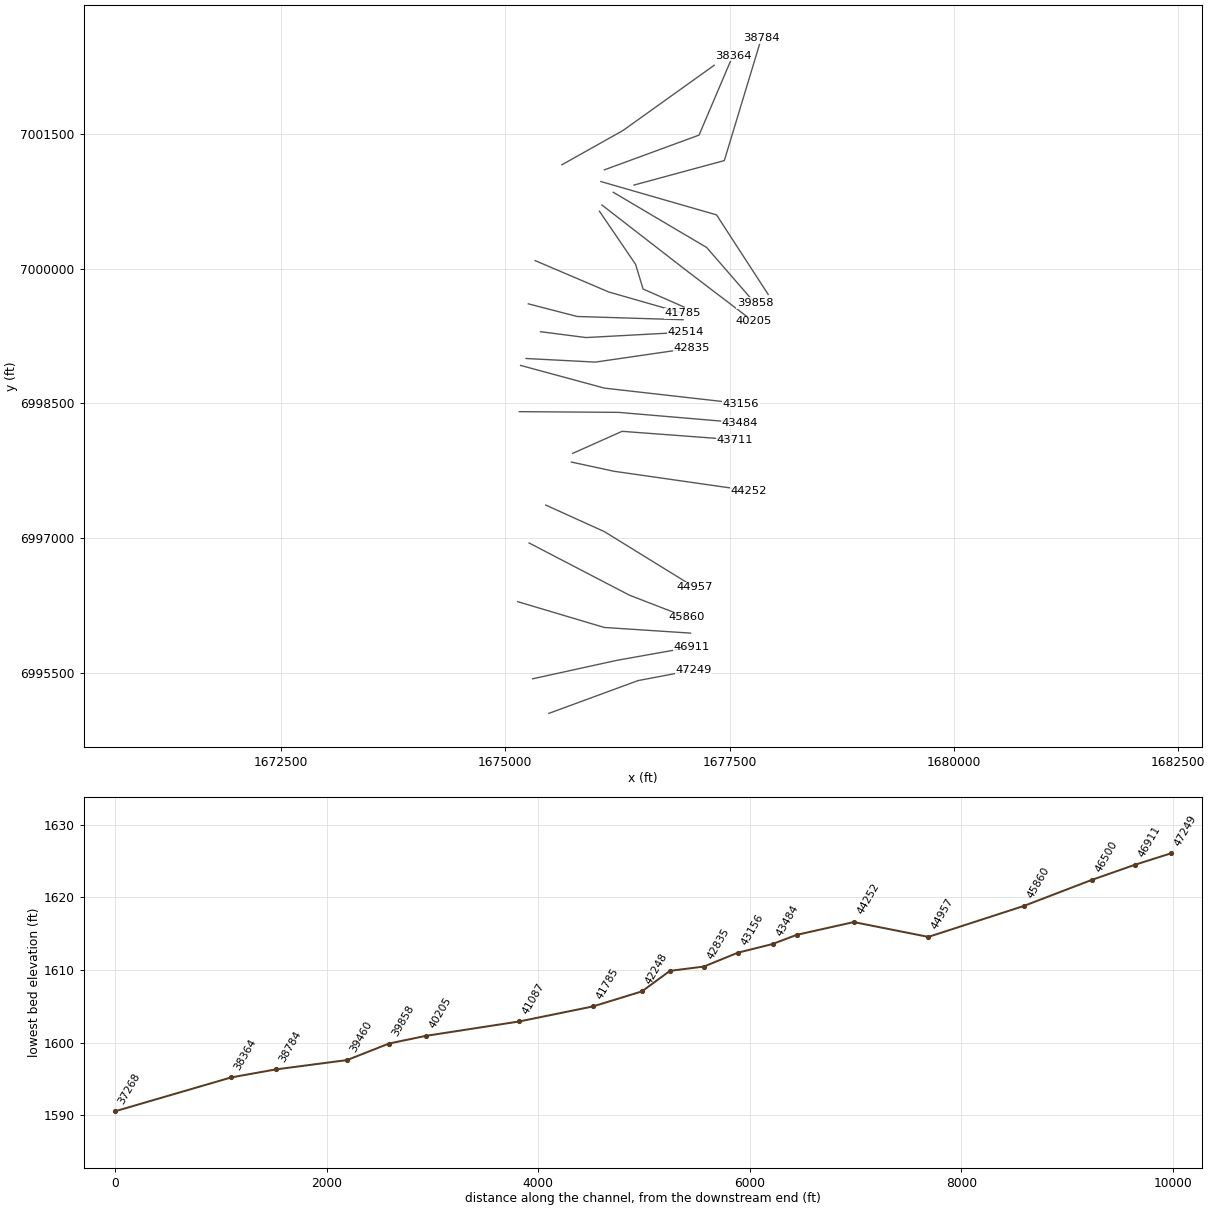
HEC-RAS study Fish Creek.prj: Fish Creek Base Level Engineering

--- Fish Creek.g01 (geometry) --- (continued)

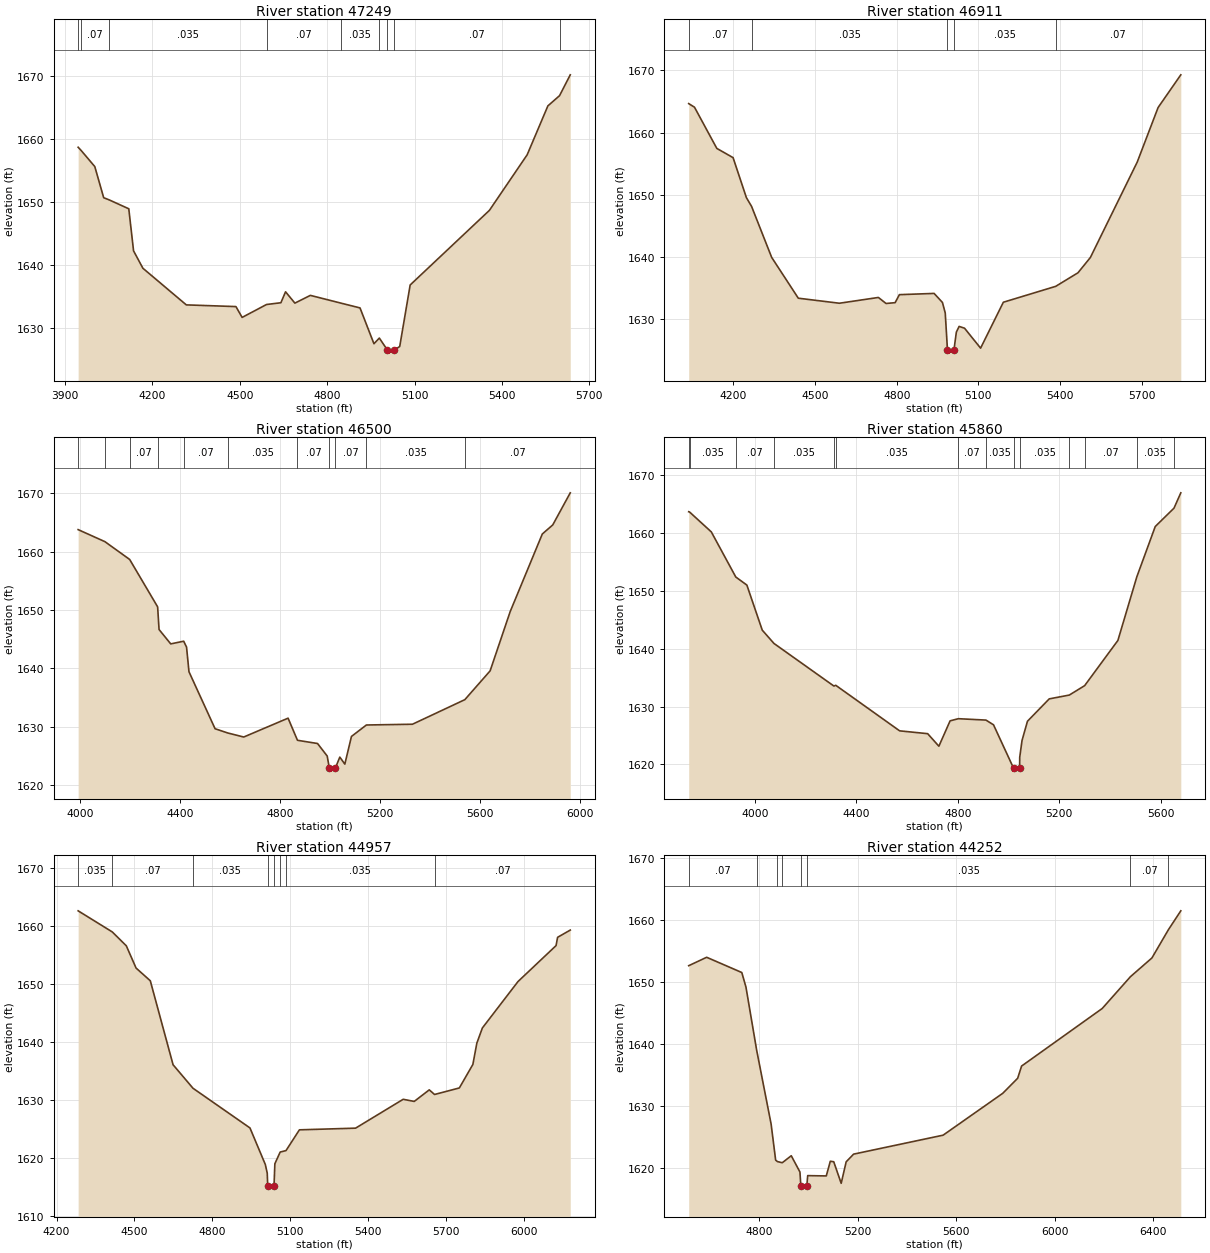
Type RM Length L Ch R = 1,47249,338,338,338
BEGIN DESCRIPTION:
Mapping XS 617921a9
END DESCRIPTION:
XS GIS Cut Line= 3
      1675486.34      6995053.27      1676480.26      6995417.85
      1677100.43      6995534.94
#Sta/Elev= 30
  3944.9 1658.75  3955.0 1658.25  4002.1 1655.68  4032.6 1650.74  4051.1 1650.40
  4118.8 1648.98  4135.2 1642.30  4167.2 1639.54  4316.3 1633.72  4486.7 1633.45
  4508.0 1631.73  4591.7 1633.78  4641.1 1634.06  4657.1 1635.80  4689.1 1634.00
  4742.3 1635.23  4847.2 1634.00  4912.8 1633.24  4960.6 1627.55  4979.1 1628.45
  5006.7 1626.56  5007.2 1626.06  5030.5 1626.56  5049.1 1627.11  5085.0 1636.88
  5357.1 1648.73  5486.7 1657.55  5557.9 1665.32  5597.9 1666.94  5634.7 1670.25
#Mann=9,-1,0
  3944.9   0.035       0  3955.0    0.07       0  4051.1   0.035       0
  4591.7    0.07       0  4847.2   0.035       0  4979.1    0.07       0
  5006.7    0.07       0  5030.5    0.07       0  5597.9   0.035       0
Bank Sta=5006.7,5030.5
Exp/Cntr=0.3,0.1

Type RM Length L Ch R = 1,46911,411,411,411
BEGIN DESCRIPTION:
Mapping XS e01623ce
END DESCRIPTION:
XS GIS Cut Line= 3
      1675304.09      6995437.39      1676245.88      6995643.54
      1677077.09      6995791.12
#Sta/Elev= 30
  4035.4 1664.66  4056.7 1664.08  4138.7 1657.45  4198.5 1655.96  4247.4 1649.53
  4266.5 1648.11  4340.3 1639.91  4438.2 1633.34  4589.1 1632.53  4732.4 1633.46
  4760.6 1632.49  4793.9 1632.62  4809.6 1633.91  4937.2 1634.11  4967.9 1632.65
  4978.1 1630.96  4986.3 1625.00  4986.8 1624.50  5010.1 1625.00  5018.9 1627.88
  5029.1 1628.80  5049.0 1628.51  5108.0 1625.30  5191.6 1632.69  5384.1 1635.25
  5465.8 1637.43  5511.4 1639.89  5683.5 1655.24  5760.3 1664.03  5843.7 1669.29
#Mann=5,-1,0
  4035.4    0.07       0  4266.5   0.035       0  4986.3   0.035       0
  5010.1   0.035       0  5384.1    0.07       0
Bank Sta=4986.3,5010.1
Exp/Cntr=0.3,0.1

Type RM Length L Ch R = 1,46500,640,640,640
BEGIN DESCRIPTION:
Mapping XS a25c8554
END DESCRIPTION:
XS GIS Cut Line= 3
      1675139.95      6996295.32      1676103.52      6996008.85
      1677064.91      6995945.91
#Sta/Elev= 30
  3993.5 1663.76  4100.5 1661.70  4199.6 1658.65  4311.5 1650.53  4317.2 1646.65
  4363.9 1644.19  4415.7 1644.65  4427.2 1643.64  4436.9 1639.42  4541.3 1629.66
  4592.3 1628.93  4656.0 1628.24  4833.4 1631.47  4870.9 1627.68  4951.2 1627.13
  4989.9 1624.98  4998.4 1622.90  4998.9 1622.40  5022.2 1622.90  5040.3 1624.80
  5060.4 1623.60  5086.9 1628.34  5146.6 1630.30  5330.9 1630.43  5540.5 1634.64
  5641.6 1639.57  5721.8 1649.71  5850.4 1663.01  5892.1 1664.56  5962.2 1670.06
#Mann=11,-1,0
  3993.5    0.07       0  4100.5   0.035       0  4199.6    0.07       0
  4311.5   0.035       0  4415.7    0.07       0  4592.3   0.035       0
  4870.9    0.07       0  4998.4    0.07       0  5022.2    0.07       0
  5146.6   0.035       0  5540.5    0.07       0
Bank Sta=4998.4,5022.2
Exp/Cntr=0.3,0.1

Type RM Length L Ch R = 1,45860,903,903,903
BEGIN DESCRIPTION:
Mapping XS 1ffa4a60
END DESCRIPTION:
XS GIS Cut Line= 3
      1675265.89      6996948.50      1676381.30      6996369.09
      1677019.01      6996122.65
#Sta/Elev= 30
  3738.4 1663.71  3741.6 1663.67  3827.6 1660.22  3924.2 1652.41  3967.8 1651.02
  4028.5 1643.22  4074.7 1640.92  4311.0 1633.55  4318.3 1633.68  4570.2 1625.80
  4680.7 1625.31  4725.0 1623.14  4769.2 1627.53  4801.8 1627.90  4910.7 1627.66
  4940.5 1626.84  5019.6 1619.33  5020.1 1618.83  5043.4 1619.33  5043.8 1621.24
  5052.9 1624.14  5074.3 1627.46  5160.1 1631.33  5239.3 1631.99  5299.8 1633.62
  5430.9 1641.44  5505.5 1652.44  5578.2 1661.15  5652.2 1664.33  5679.0 1666.98
#Mann=14,-1,0
  3738.4    0.07       0  3741.6   0.035       0  3924.2    0.07       0
  4074.7   0.035       0  4311.0    0.07       0  4318.3   0.035       0
  4801.8    0.07       0  4910.7   0.035       0  5019.6   0.035       0
  5043.4   0.035       0  5239.3   0.035       0  5299.8    0.07       0
  5505.5   0.035       0  5652.2    0.07       0
Bank Sta=5019.6,5043.4
Exp/Cntr=0.3,0.1

Type RM Length L Ch R = 1,44957,705,705,705
BEGIN DESCRIPTION:
Mapping XS 6a2b065a
END DESCRIPTION:
XS GIS Cut Line= 3
      1675451.57      6997369.83      1676104.82      6997074.68
      1677109.59      6996456.19
#Sta/Elev= 30
  4283.3 1662.68  4414.9 1659.03  4469.0 1656.63  4506.5 1652.79  4561.4 1650.59
  4649.2 1636.07  4725.9 1632.01  4945.5 1625.15  5004.8 1618.82  5012.1 1617.34
  5014.0 1615.07  5014.5 1614.57  5038.2 1615.07  5041.5 1618.96  5062.0 1620.98
  5084.4 1621.23  5136.1 1624.82  5352.6 1625.11  5536.1 1630.10  5578.6 1629.73
  5636.6 1631.73  5657.0 1630.93  5752.5 1632.06  5804.6 1636.12  5820.0 1639.81
  5841.3 1642.43  5978.5 1650.45  6125.3 1656.67  6131.2 1658.10  6180.0 1659.35
#Mann=8,-1,0
  4283.3   0.035       0  4414.9    0.07       0  4725.9   0.035       0
  5014.0   0.035       0  5038.2   0.035       0  5062.0    0.07       0
  5084.4   0.035       0  5657.0    0.07       0
Bank Sta=5014,5038.2
Exp/Cntr=0.3,0.1

Type RM Length L Ch R = 1,44252,541,541,541
BEGIN DESCRIPTION:
Mapping XS 43fe0c2a
END DESCRIPTION:
XS GIS Cut Line= 3
      1675737.56      6997848.14      1676210.62      6997746.15
      1677711.21      6997531.47
#Sta/Elev= 30
  4513.0 1652.68  4586.0 1654.04  4728.8 1651.58  4745.7 1649.23  4789.3 1639.02
  4848.0 1627.10  4866.4 1621.29  4873.6 1621.06  4893.2 1620.87  4929.8 1622.00
  4965.0 1619.38  4968.8 1617.11  4969.3 1616.61  4993.0 1617.11  4996.6 1618.79
  5072.1 1618.74  5088.5 1621.11  5102.4 1621.03  5132.7 1617.55  5152.9 1621.02
  5183.2 1622.26  5546.9 1625.32  5789.3 1632.08  5849.9 1634.51  5865.8 1636.48
  6193.4 1645.77  6308.2 1650.91  6395.4 1653.93  6462.4 1658.49  6512.8 1661.54
#Mann=8,-1,0
  4513.0    0.07       0  4789.3   0.035       0  4873.6    0.07       0
  4893.2   0.035       0  4968.8   0.035       0  4993.0   0.035       0
  6308.2    0.07       0  6462.4   0.035       0
Bank Sta=4968.8,4993
Exp/Cntr=0.3,0.1

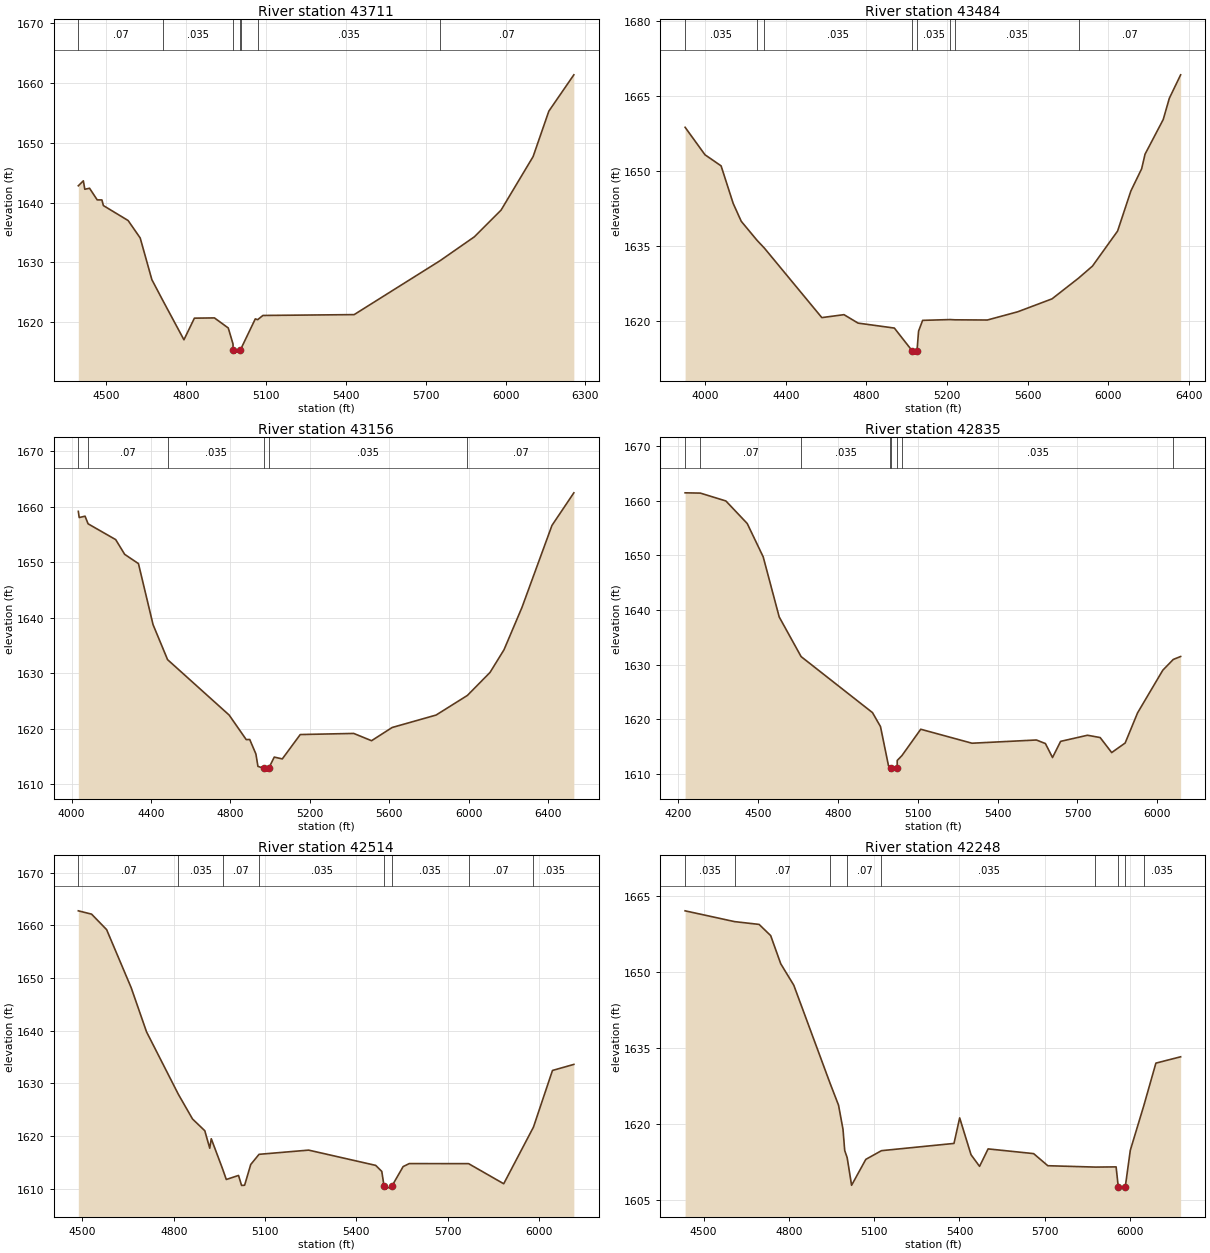
Type RM Length L Ch R = 1,43711,227,227,227
BEGIN DESCRIPTION:
Mapping XS 65459006
END DESCRIPTION:
XS GIS Cut Line= 3
      1675752.79      6997945.26      1676302.27      6998190.06
      1677557.43      6998096.31
#Sta/Elev= 30
  4396.1 1642.79  4415.0 1643.62  4420.5 1642.21  4438.3 1642.38  4467.0 1640.44
  4484.7 1640.43  4490.2 1639.49  4583.1 1636.99  4628.4 1634.08  4672.2 1627.12
  4712.3 1623.73  4792.6 1617.08  4831.9 1620.69  4907.1 1620.73  4959.0 1619.05
  4976.8 1616.38  4977.4 1615.35  4977.9 1614.85  5001.9 1615.35  5007.1 1615.62
  5060.5 1620.57  5069.3 1620.43  5089.0 1621.14  5431.6 1621.28  5754.0 1630.28
  5882.8 1634.27  5983.1 1638.73  6103.4 1647.67  6162.5 1655.26  6256.3 1661.32
#Mann=7,-1,0
  4396.1    0.07       0  4712.3   0.035       0  4977.4   0.035       0
  5001.9   0.035       0  5007.1    0.07       0  5069.3   0.035       0
  5754.0    0.07       0
Bank Sta=4977.4,5001.9
Exp/Cntr=0.3,0.1

Type RM Length L Ch R = 1,43484,328,328,328
BEGIN DESCRIPTION:
Mapping XS 3d01c6b3
END DESCRIPTION:
XS GIS Cut Line= 3
      1675156.41      6998408.81      1676260.60      6998400.99
      1677611.04      6998286.51
#Sta/Elev= 30
  3900.4 1658.74  3999.0 1653.25  4079.0 1651.03  4139.0 1643.52  4179.0 1639.95
  4257.5 1636.14  4294.0 1634.58  4579.0 1620.69  4689.0 1621.28  4759.0 1619.59
  4939.0 1618.60  5026.7 1614.09  5027.2 1613.59  5051.5 1614.09  5059.2 1617.99
  5079.3 1620.14  5216.0 1620.30  5240.1 1620.25  5400.4 1620.21  5551.0 1621.85
  5721.6 1624.44  5853.4 1628.59  5922.3 1630.99  6047.0 1638.00  6113.0 1646.02
  6166.4 1650.45  6183.2 1653.36  6273.5 1660.30  6303.7 1664.53  6359.9 1669.23
#Mann=8,-1,0
  3900.4   0.035       0  4257.5    0.07       0  4294.0   0.035       0
  5026.7   0.035       0  5051.5   0.035       0  5216.0    0.07       0
  5240.1   0.035       0  5853.4    0.07       0
Bank Sta=5026.7,5051.5
Exp/Cntr=0.3,0.1

Type RM Length L Ch R = 1,43156,321,321,321
BEGIN DESCRIPTION:
Mapping XS bd62a572
END DESCRIPTION:
XS GIS Cut Line= 3
      1675171.40      6998923.03      1676106.26      6998670.44
      1677624.48      6998498.56
#Sta/Elev= 30
  4033.8 1659.19  4038.3 1658.08  4067.8 1658.32  4083.0 1656.95  4222.2 1654.10
  4267.3 1651.45  4336.7 1649.78  4410.4 1638.78  4483.5 1632.48  4793.7 1622.50
  4879.6 1618.08  4897.3 1618.10  4928.4 1615.49  4938.7 1613.26  4967.7 1612.90
  4968.2 1612.40  4992.6 1612.90  5021.0 1614.93  5061.3 1614.60  5151.9 1618.99
  5421.2 1619.19  5511.0 1617.88  5614.8 1620.26  5836.2 1622.50  5994.0 1626.04
  6107.9 1630.18  6178.4 1634.27  6269.0 1641.91  6419.9 1656.66  6530.1 1662.53
#Mann=6,-1,0
  4033.8   0.035       0  4083.0    0.07       0  4483.5   0.035       0
  4967.7   0.035       0  4992.6   0.035       0  5994.0    0.07       0
Bank Sta=4967.7,4992.6
Exp/Cntr=0.3,0.1

Type RM Length L Ch R = 1,42835,321,321,321
BEGIN DESCRIPTION:
Mapping XS 1ff15bdf
END DESCRIPTION:
XS GIS Cut Line= 3
      1675231.96      6998999.95      1676004.53      6998960.02
      1677081.28      6999116.07
#Sta/Elev= 30
  4225.9 1661.45  4283.1 1661.40  4379.1 1659.96  4459.3 1655.83  4519.3 1649.72
  4579.4 1638.72  4661.7 1631.46  4929.9 1621.20  4959.9 1618.65  4990.0 1611.48
  4995.5 1611.33  4997.6 1610.99  4998.1 1610.49  5022.5 1610.99  5022.8 1612.44
  5040.4 1613.33  5111.1 1618.16  5303.7 1615.60  5545.6 1616.19  5579.5 1615.54
  5606.2 1612.98  5636.6 1615.94  5737.6 1617.06  5785.1 1616.64  5828.5 1613.89
  5879.1 1615.64  5925.6 1621.15  6020.5 1628.97  6059.8 1630.94  6087.5 1631.48
#Mann=8,-1,0
  4225.9   0.035       0  4283.1    0.07       0  4661.7   0.035       0
  4995.5    0.07       0  4997.6    0.07       0  5022.5    0.07       0
  5040.4   0.035       0  6059.8    0.07       0
Bank Sta=4997.6,5022.5
Exp/Cntr=0.3,0.1

Type RM Length L Ch R = 1,42514,266,266,266
BEGIN DESCRIPTION:
Mapping XS c108f179
END DESCRIPTION:
XS GIS Cut Line= 3
      1675392.76      6999298.04      1675900.53      6999232.94
      1677015.10      6999292.83
#Sta/Elev= 30
  4486.3 1662.76  4529.9 1662.13  4579.3 1659.19  4660.0 1648.16  4710.4 1639.78
  4815.1 1627.90  4861.6 1623.22  4901.9 1620.99  4918.1 1617.67  4923.1 1619.47
  4960.1 1613.78  4972.5 1611.73  5012.7 1612.50  5022.7 1610.60  5032.7 1610.64
  5052.8 1614.58  5080.1 1616.51  5243.0 1617.31  5463.4 1614.41  5483.4 1613.26
  5491.0 1610.40  5491.5 1609.90  5515.9 1610.40  5553.5 1614.18  5573.5 1614.75
  5768.6 1614.74  5884.0 1610.92  5981.7 1621.68  6044.2 1632.44  6114.4 1633.59
#Mann=8,-1,0
  4486.3    0.07       0  4815.1   0.035       0  4960.1    0.07       0
  5080.1   0.035       0  5491.0    0.07       0  5515.9   0.035       0
  5768.6    0.07       0  5981.7   0.035       0
Bank Sta=5491,5515.9
Exp/Cntr=0.3,0.1

Type RM Length L Ch R = 1,42248,463,463,463
BEGIN DESCRIPTION:
Mapping XS 42644b85
END DESCRIPTION:
XS GIS Cut Line= 3
      1675257.27      6999607.95      1675801.58      6999467.31
      1676981.94      6999430.91
#Sta/Elev= 30
  4434.8 1662.00  4608.7 1659.87  4695.1 1659.32  4735.8 1657.11  4771.2 1651.55
  4817.1 1647.32  4944.8 1627.95  4974.5 1623.64  4990.2 1618.88  4996.2 1614.70
  5004.9 1613.27  5020.4 1607.83  5070.4 1612.94  5125.5 1614.66  5380.6 1616.09
  5400.6 1621.13  5440.6 1613.86  5470.6 1611.56  5500.6 1615.01  5660.7 1614.08
  5710.7 1611.69  5878.1 1611.42  5950.9 1611.46  5958.4 1607.57  5958.9 1607.07
  5983.3 1607.57  6000.9 1614.75  6048.2 1623.52  6090.9 1631.94  6177.9 1633.19
#Mann=9,-1,0
  4434.8   0.035       0  4608.7    0.07       0  4944.8   0.035       0
  5004.9    0.07       0  5125.5   0.035       0  5878.1    0.07       0
  5958.4   0.035       0  5983.3    0.07       0  6048.2   0.035       0
Bank Sta=5958.4,5983.3
Exp/Cntr=0.3,0.1

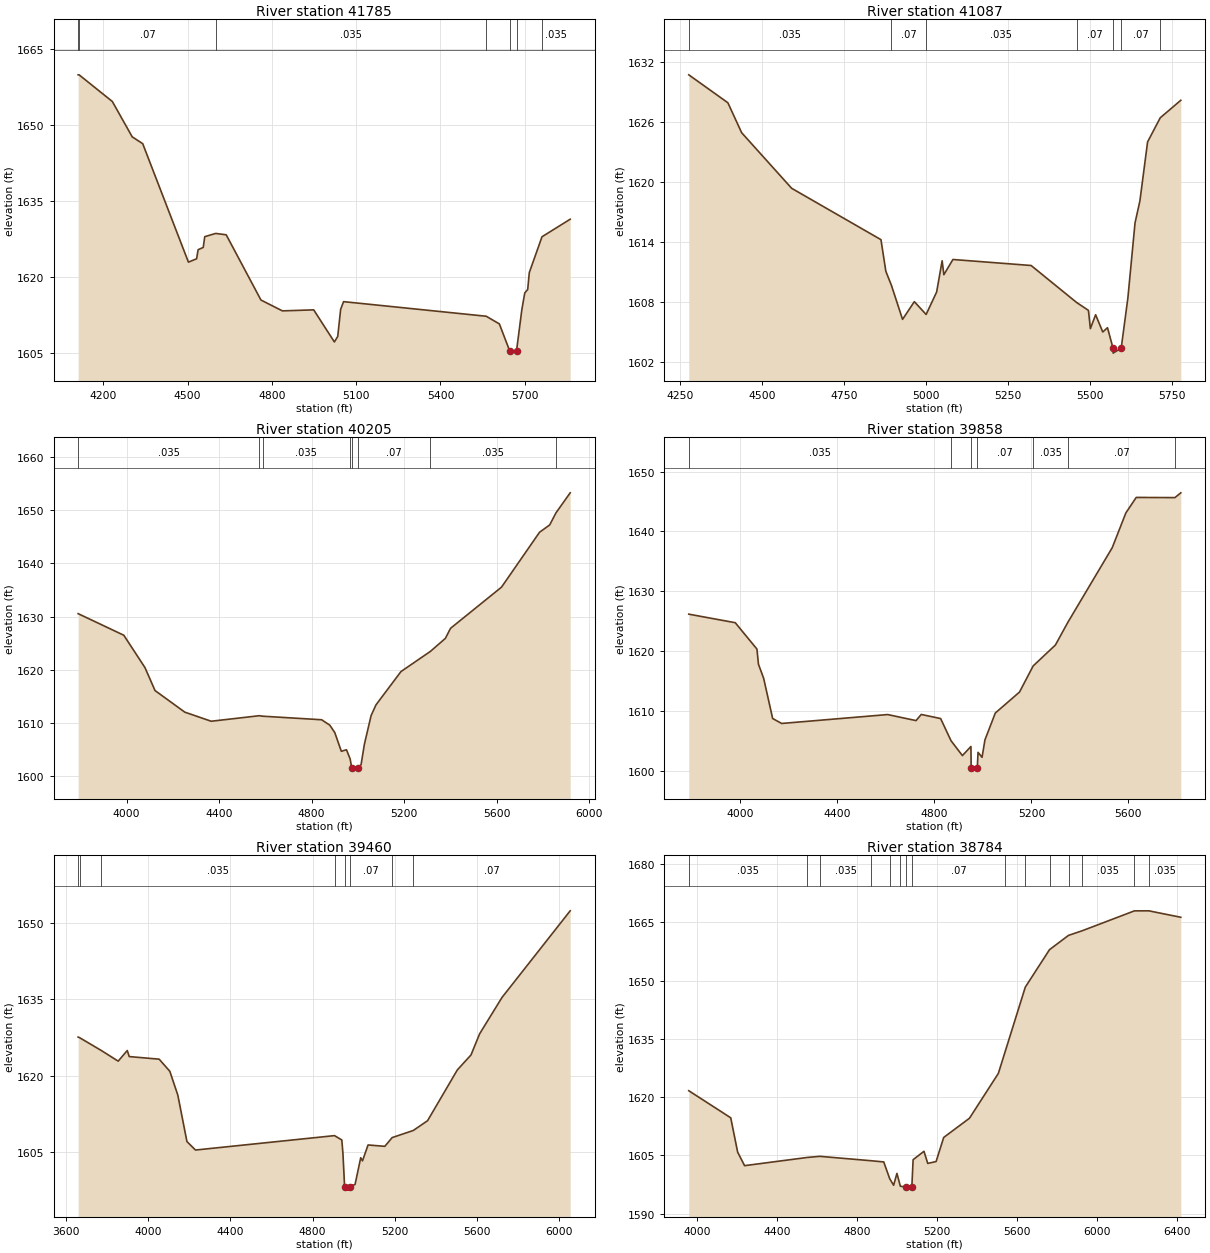
Type RM Length L Ch R = 1,41785,698,698,698
BEGIN DESCRIPTION:
Mapping XS 54fd50cb
END DESCRIPTION:
XS GIS Cut Line= 3
      1675333.49      7000088.62      1676153.79      6999739.67
      1676980.38      6999503.13
#Sta/Elev= 30
  4110.5 1659.87  4114.1 1659.86  4232.1 1654.62  4303.0 1647.64  4340.3 1646.30
  4503.0 1622.94  4532.1 1623.60  4537.5 1625.39  4555.7 1625.84  4561.1 1627.96
  4600.0 1628.60  4637.5 1628.33  4761.1 1615.47  4837.5 1613.33  4948.9 1613.53
  5022.5 1607.20  5034.4 1608.29  5044.8 1613.64  5055.2 1615.15  5563.0 1612.27
  5609.7 1610.76  5646.0 1605.50  5646.5 1605.00  5670.9 1605.50  5689.7 1613.58
  5700.1 1616.87  5710.5 1617.54  5716.2 1620.88  5761.4 1627.94  5861.7 1631.40
#Mann=7,-1,0
  4110.5   0.035       0  4114.1    0.07       0  4600.0   0.035       0
  5563.0    0.07       0  5646.0   0.035       0  5670.9    0.07       0
  5761.4   0.035       0
Bank Sta=5646,5670.9
Exp/Cntr=0.3,0.1

Type RM Length L Ch R = 1,41087,882,882,882
BEGIN DESCRIPTION:
Mapping XS c229b531
END DESCRIPTION:
XS GIS Cut Line= 4
      1676050.08      7000637.47      1676452.87      7000047.17
      1676536.20      6999772.87      1676992.77      6999572.26
#Sta/Elev= 30
  4275.7 1630.72  4394.9 1627.93  4436.9 1624.94  4589.3 1619.39  4861.6 1614.26
  4876.5 1611.10  4893.5 1609.70  4927.4 1606.30  4963.3 1608.07  4999.3 1606.79
  5031.3 1609.03  5048.1 1612.15  5053.3 1610.76  5081.0 1612.28  5319.4 1611.68
  5457.9 1607.99  5494.1 1607.20  5500.0 1605.38  5516.0 1606.76  5537.8 1605.04
  5552.2 1605.47  5569.0 1603.43  5569.5 1602.93  5594.0 1603.43  5614.3 1608.43
  5636.1 1615.93  5651.0 1618.13  5674.4 1624.02  5713.0 1626.43  5775.7 1628.18
#Mann=7,-1,0
  4275.7   0.035       0  4893.5    0.07       0  4999.3   0.035       0
  5457.9    0.07       0  5569.0   0.035       0  5594.0    0.07       0
  5713.0   0.035       0
Bank Sta=5569,5594
Exp/Cntr=0.3,0.1

Type RM Length L Ch R = 1,40205,347,347,347
BEGIN DESCRIPTION:
Mapping XS 0e12c115
END DESCRIPTION:
XS GIS Cut Line= 3
      1676077.85      7000706.91      1677029.26      6999970.78
      1677764.53      6999412.40
#Sta/Elev= 30
  3790.9 1630.56  3988.3 1626.50  4079.8 1620.41  4123.2 1616.10  4251.8 1612.04
  4365.9 1610.33  4573.7 1611.37  4587.8 1611.28  4843.1 1610.61  4878.4 1609.59
  4899.9 1608.20  4928.2 1604.68  4950.5 1604.97  4966.4 1603.23  4973.5 1601.45
  4974.0 1600.95  4998.8 1601.45  5013.6 1602.18  5027.8 1606.00  5056.9 1611.40
  5077.8 1613.40  5185.9 1619.67  5313.3 1623.47  5377.8 1625.91  5400.1 1627.80
  5620.5 1635.55  5784.8 1645.87  5828.5 1647.24  5855.7 1649.51  5917.1 1653.28
#Mann=8,-1,0
  3790.9   0.035       0  4573.7    0.07       0  4587.8   0.035       0
  4966.4    0.07       0  4973.5    0.07       0  4998.8    0.07       0
  5313.3   0.035       0  5855.7    0.07       0
Bank Sta=4973.5,4998.8
Exp/Cntr=0.3,0.1

Type RM Length L Ch R = 1,39858,398,398,398
BEGIN DESCRIPTION:
Mapping XS bf263df4
END DESCRIPTION:
XS GIS Cut Line= 3
      1676202.89      7000849.24      1677244.54      7000234.67
      1677782.75      6999616.60
#Sta/Elev= 30
  3787.0 1626.15  3978.7 1624.72  4068.1 1620.31  4074.4 1617.77  4095.8 1615.42
  4132.9 1608.70  4170.0 1607.87  4607.1 1609.36  4724.2 1608.35  4745.6 1609.38
  4825.6 1608.69  4868.5 1604.98  4915.4 1602.50  4950.5 1604.02  4951.5 1600.40
  4952.0 1599.90  4976.8 1600.40  4979.8 1603.04  4996.4 1602.21  5008.3 1605.13
  5051.1 1609.62  5150.8 1613.12  5207.1 1617.49  5298.9 1620.99  5350.0 1624.77
  5533.4 1637.28  5589.4 1643.08  5632.1 1645.67  5791.7 1645.64  5816.0 1646.44
#Mann=7,-1,0
  3787.0   0.035       0  4868.5    0.07       0  4951.5    0.07       0
  4976.8    0.07       0  5207.1   0.035       0  5350.0    0.07       0
  5791.7   0.035       0
Bank Sta=4951.5,4976.8
Exp/Cntr=0.3,0.1

Type RM Length L Ch R = 1,39460,676,676,676
BEGIN DESCRIPTION:
Fish Creek 68.0
END DESCRIPTION:
XS GIS Cut Line= 3
      1676065.86      7000967.86      1677354.91      7000597.13
      1677929.99      6999713.01
#Sta/Elev= 30
  3658.7 1627.58  3666.8 1627.43  3771.0 1624.94  3853.7 1622.83  3897.9 1624.92
  3907.5 1623.73  4053.2 1623.22  4105.2 1620.83  4144.1 1616.14  4188.5 1606.99
  4230.1 1605.32  4907.2 1608.16  4942.7 1607.30  4948.1 1604.69  4956.2 1598.12
  4956.7 1597.62  4981.5 1598.12  5007.1 1598.53  5034.7 1603.80  5043.4 1603.19
  5070.5 1606.32  5152.1 1606.05  5187.8 1607.77  5291.0 1609.18  5360.3 1611.10
  5505.2 1621.10  5571.6 1624.04  5613.9 1628.22  5722.6 1635.37  6054.7 1652.44
#Mann=8,-1,0
  3658.7   0.035       0  3666.8    0.07       0  3771.0   0.035       0
  4907.2    0.07       0  4956.2    0.07       0  4981.5    0.07       0
  5187.8   0.035       0  5291.0    0.07       0
Bank Sta=4956.2,4981.5
Exp/Cntr=0.3,0.1

Type RM Length L Ch R = 1,38784,420,420,420
BEGIN DESCRIPTION:
Fish Creek 66.0
END DESCRIPTION:
XS GIS Cut Line= 3
      1676434.80      7000928.79      1677441.88      7001201.32
      1677854.08      7002560.70
#Sta/Elev= 30
  3956.7 1621.66  4166.8 1614.69  4201.4 1605.86  4236.1 1602.37  4551.1 1604.49
  4612.7 1604.77  4871.4 1603.63  4932.9 1603.33  4963.1 1598.98  4982.5 1597.33
  4999.0 1600.38  5016.1 1597.09  5042.8 1596.83  5043.3 1596.33  5073.6 1596.83
  5080.1 1603.91  5134.5 1606.07  5153.3 1602.95  5195.1 1603.43  5233.2 1609.63
  5362.3 1614.58  5506.9 1626.12  5540.5 1631.65  5641.8 1648.32  5763.0 1657.96
  5858.2 1661.64  5927.8 1662.85  6188.2 1667.95  6260.4 1667.96  6420.5 1666.30
#Mann=15,-1,0
  3956.7   0.035       0  4551.1    0.07       0  4612.7   0.035       0
  4871.4    0.07       0  4963.1   0.035       0  5016.1    0.07       0
  5042.8   0.035       0  5073.6    0.07       0  5540.5   0.035       0
  5641.8    0.07       0  5763.0   0.035       0  5858.2    0.07       0
  5927.8   0.035       0  6188.2    0.07       0  6260.4   0.035       0
Bank Sta=5042.8,5073.6
Exp/Cntr=0.3,0.1

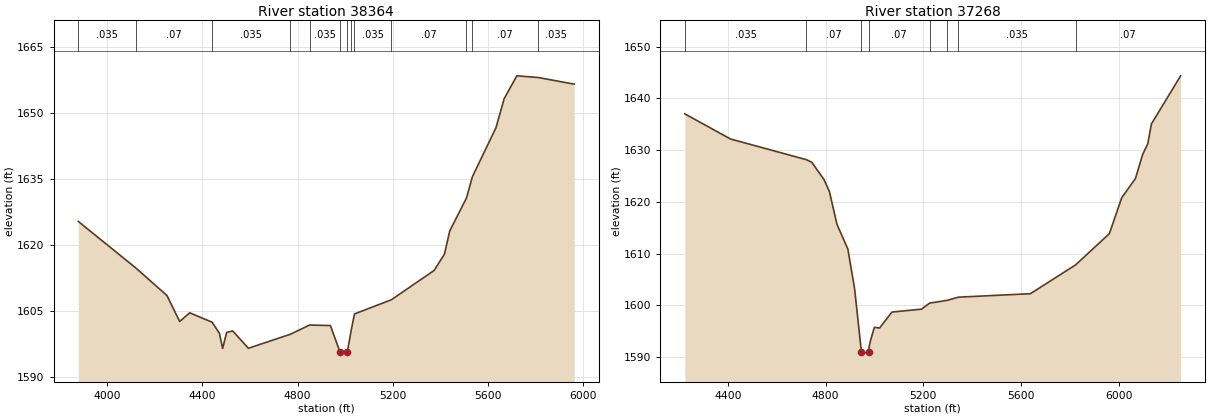
Type RM Length L Ch R = 1,38364,1096,1096,1096
BEGIN DESCRIPTION:
Mapping XS e1c27b4f
END DESCRIPTION:
XS GIS Cut Line= 3
      1676105.00      7001098.08      1677159.65      7001484.35
      1677537.24      7002369.74
#Sta/Elev= 30
  3877.9 1625.41  4121.3 1614.76  4250.6 1608.57  4304.2 1602.66  4346.5 1604.63
  4440.9 1602.48  4471.4 1599.97  4484.9 1596.53  4501.9 1600.18  4527.1 1600.51
  4593.4 1596.56  4769.8 1599.75  4850.8 1601.85  4938.3 1601.73  4978.5 1595.73
  4979.0 1595.23  5009.4 1595.73  5026.5 1600.88  5039.6 1604.37  5194.8 1607.60
  5374.7 1614.27  5418.1 1617.99  5440.3 1623.26  5510.6 1630.75  5535.7 1635.61
  5634.7 1646.73  5669.2 1653.35  5722.5 1658.54  5812.1 1658.16  5963.6 1656.65
#Mann=13,-1,0
  3877.9   0.035       0  4121.3    0.07       0  4440.9   0.035       0
  4769.8    0.07       0  4850.8   0.035       0  4978.5   0.035       0
  5009.4   0.035       0  5026.5    0.07       0  5039.6   0.035       0
  5194.8    0.07       0  5510.6   0.035       0  5535.7    0.07       0
  5812.1   0.035       0
Bank Sta=4978.5,5009.4
Exp/Cntr=0.3,0.1

Type RM Length L Ch R = 1,37268,461,461,461
BEGIN DESCRIPTION:
Mapping XS be6adde7
END DESCRIPTION:
XS GIS Cut Line= 3
      1675631.89      7001154.50      1676313.29      7001536.43
      1677328.92      7002261.26
#Sta/Elev= 30
  4223.8 1637.03  4410.8 1632.17  4721.2 1628.17  4743.2 1627.68  4794.1 1624.28
  4815.8 1621.96  4846.4 1615.68  4891.1 1610.89  4918.5 1603.27  4946.4 1591.08
  4946.9 1590.58  4977.4 1591.08  4977.9 1591.93  4984.0 1593.26  4999.6 1595.76
  5020.9 1595.63  5071.3 1598.71  5192.9 1599.28  5225.4 1600.44  5297.6 1600.98
  5343.6 1601.59  5637.9 1602.26  5822.9 1607.83  5961.1 1613.87  6011.5 1620.79
  6068.0 1624.55  6097.5 1629.20  6118.4 1631.26  6133.2 1635.08  6252.7 1644.38
#Mann=8,-1,0
  4223.8   0.035       0  4721.2    0.07       0  4946.4    0.07       0
  4977.4    0.07       0  5225.4   0.035       0  5297.6    0.07       0
  5343.6   0.035       0  5822.9    0.07       0
Bank Sta=4946.4,4977.4
Exp/Cntr=0.3,0.1