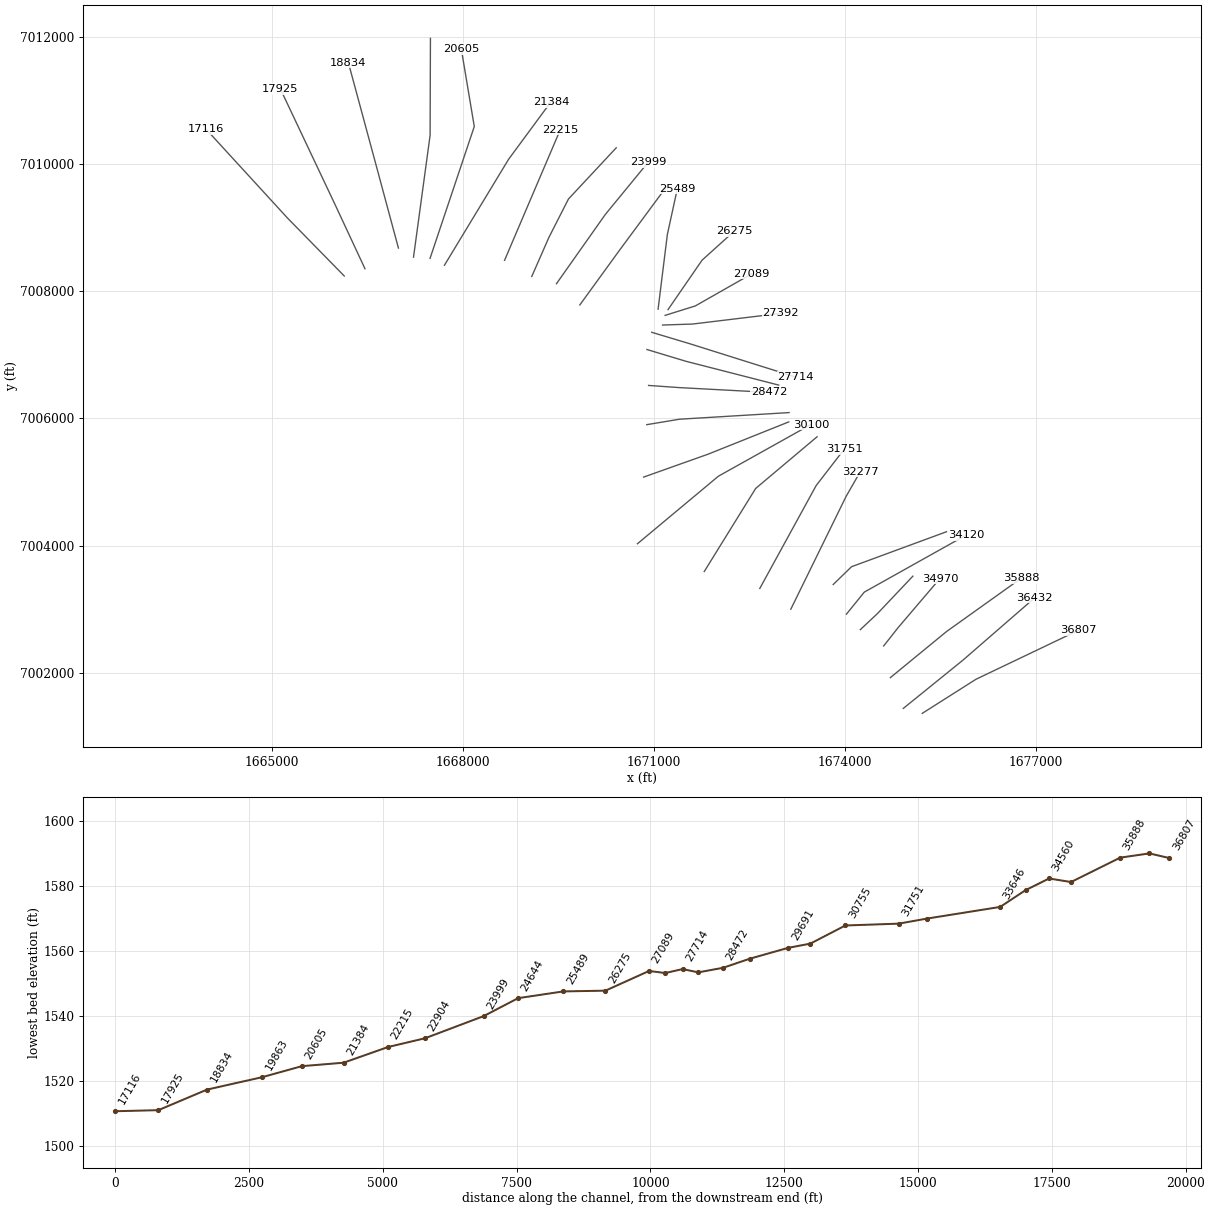
HEC-RAS study Fish Creek.prj: Fish Creek Base Level Engineering

--- Fish Creek.g01 (geometry) --- (continued)

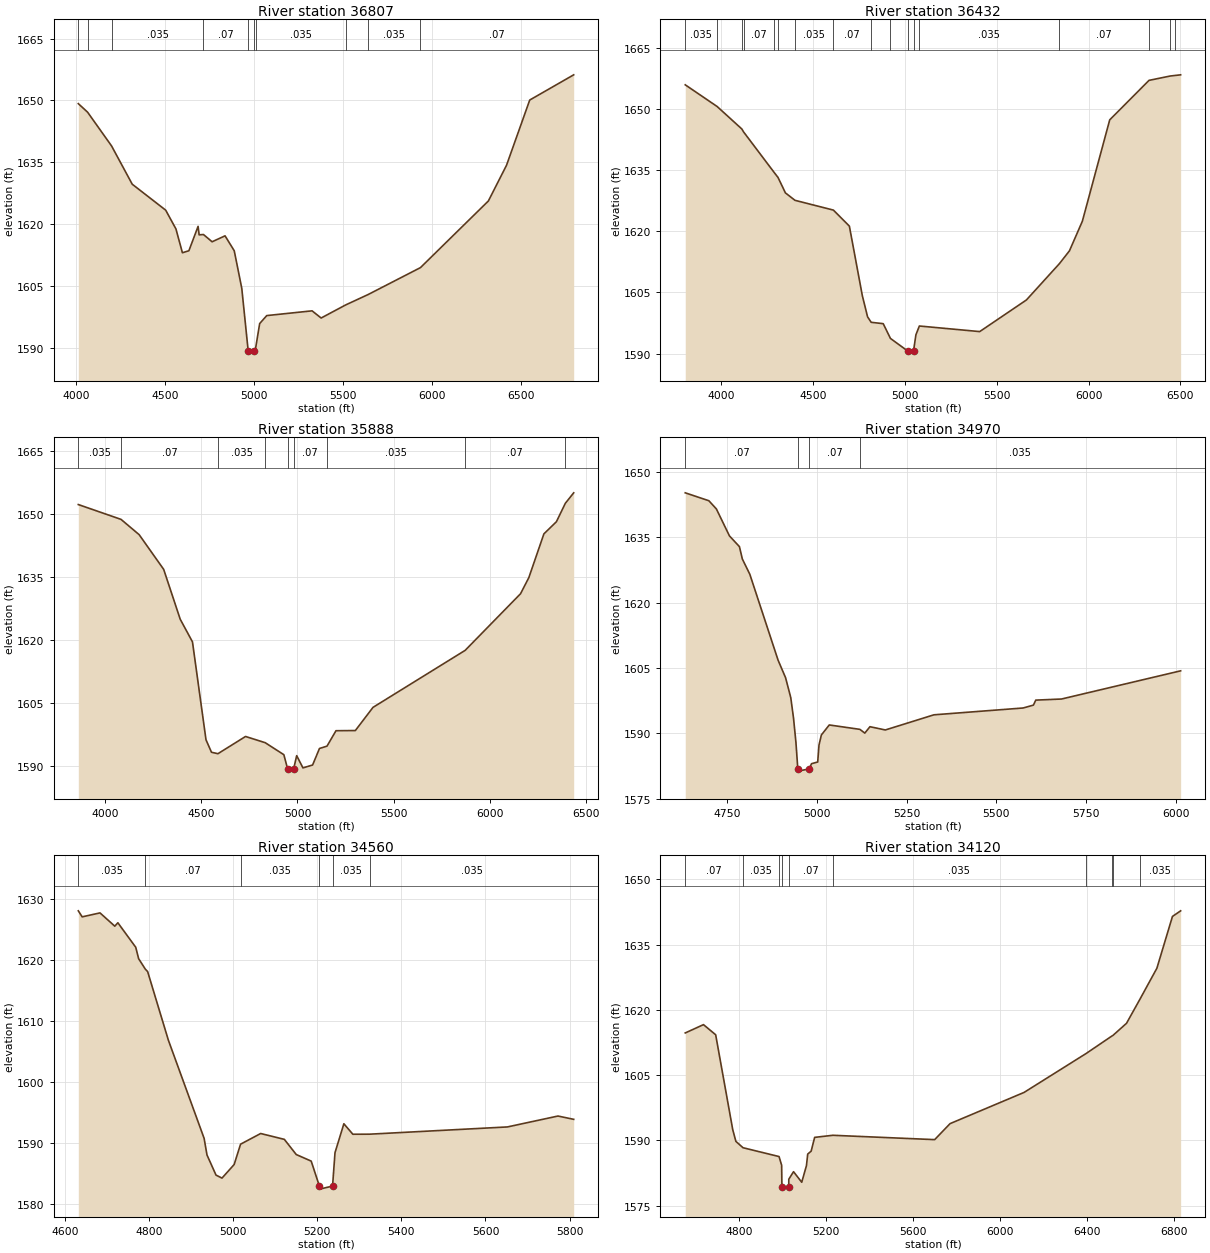
Type RM Length L Ch R = 1,36807,375,375,375
BEGIN DESCRIPTION:
Mapping XS 2d889602
END DESCRIPTION:
XS GIS Cut Line= 3
      1675214.37      7001360.24      1676058.08      7001896.67
      1677667.49      7002667.52
#Sta/Elev= 30
  4010.8 1649.23  4062.9 1647.16  4197.5 1638.98  4313.9 1629.68  4501.9 1623.38
  4559.5 1618.83  4595.9 1613.05  4632.3 1613.53  4684.0 1619.45  4689.9 1617.39
  4714.2 1617.47  4762.8 1615.71  4835.6 1617.15  4887.2 1613.53  4929.6 1604.42
  4965.7 1589.19  4966.2 1588.69  4996.7 1589.19  5007.6 1589.95  5030.1 1595.86
  5069.9 1597.80  5324.7 1598.95  5375.6 1597.21  5512.8 1600.37  5639.9 1602.91
  5933.9 1609.44  6315.6 1625.61  6417.6 1634.28  6548.0 1650.10  6795.1 1656.22
#Mann=10,-1,0
  4010.8   0.035       0  4062.9    0.07       0  4197.5   0.035       0
  4714.2    0.07       0  4965.7    0.07       0  4996.7    0.07       0
  5007.6   0.035       0  5512.8    0.07       0  5639.9   0.035       0
  5933.9    0.07       0
Bank Sta=4965.7,4996.7
Exp/Cntr=0.3,0.1

Type RM Length L Ch R = 1,36432,544,544,544
BEGIN DESCRIPTION:
Mapping XS 12a6a9c5
END DESCRIPTION:
XS GIS Cut Line= 3
      1674917.49      7001438.37      1675854.96      7002198.76
      1676979.95      7003177.91
#Sta/Elev= 30
  3802.7 1655.91  3976.1 1650.60  4110.9 1645.08  4120.3 1644.37  4286.5 1634.45
  4308.0 1633.20  4348.3 1629.41  4400.4 1627.59  4609.8 1625.19  4696.7 1621.26
  4767.1 1604.25  4795.8 1599.02  4815.4 1597.68  4881.1 1597.34  4920.5 1593.72
  5015.1 1590.62  5015.6 1590.12  5046.1 1590.62  5059.1 1594.61  5078.0 1596.77
  5406.6 1595.40  5661.0 1603.15  5841.0 1612.07  5895.6 1615.21  5965.8 1622.46
  6114.9 1647.32  6328.9 1657.00  6443.5 1658.06  6470.2 1658.20  6501.2 1658.36
#Mann=17,-1,0
  3802.7   0.035       0  3976.1    0.07       0  4110.9   0.035       0
  4120.3    0.07       0  4286.5   0.035       0  4308.0    0.07       0
  4400.4   0.035       0  4609.8    0.07       0  4815.4   0.035       0
  4920.5    0.07       0  5015.1    0.07       0  5046.1    0.07       0
  5078.0   0.035       0  5841.0    0.07       0  6328.9   0.035       0
  6443.5    0.07       0  6470.2   0.035       0
Bank Sta=5015.1,5046.1
Exp/Cntr=0.3,0.1

Type RM Length L Ch R = 1,35888,918,918,918
BEGIN DESCRIPTION:
Mapping XS eb1fadea
END DESCRIPTION:
XS GIS Cut Line= 3
      1674714.33      7001922.71      1675594.54      7002646.67
      1676764.89      7003484.13
#Sta/Elev= 30
  3859.0 1652.27  4081.4 1648.74  4175.7 1645.10  4303.4 1636.84  4389.5 1624.97
  4453.3 1619.58  4523.7 1596.27  4552.3 1593.30  4585.9 1592.96  4729.6 1597.06
  4831.8 1595.58  4929.0 1592.72  4948.7 1589.31  4949.2 1588.81  4979.7 1589.31
  4995.8 1592.49  5028.4 1589.58  5078.7 1590.27  5114.4 1594.20  5153.6 1594.76
  5200.4 1598.43  5301.1 1598.47  5393.2 1603.99  5872.8 1617.56  6161.1 1631.04
  6204.3 1634.88  6282.7 1645.29  6347.8 1648.18  6394.3 1652.57  6437.8 1655.06
#Mann=9,-1,0
  3859.0   0.035       0  4081.4    0.07       0  4585.9   0.035       0
  4831.8    0.07       0  4948.7    0.07       0  4979.7    0.07       0
  5153.6   0.035       0  5872.8    0.07       0  6394.3   0.035       0
Bank Sta=4948.7,4979.7
Exp/Cntr=0.3,0.1

Type RM Length L Ch R = 1,34970,410,410,410
BEGIN DESCRIPTION:
Mapping XS b74b196f
END DESCRIPTION:
XS GIS Cut Line= 3
      1674609.39      7002421.28      1674835.27      7002708.50
      1675491.11      7003479.89
#Sta/Elev= 30
  4634.6 1645.26  4700.3 1643.44  4721.2 1641.55  4757.6 1635.35  4785.3 1632.89
  4793.4 1630.05  4814.2 1626.54  4892.8 1606.80  4913.6 1602.78  4928.1 1598.19
  4935.8 1593.45  4942.5 1587.85  4947.7 1581.80  4948.2 1581.30  4979.0 1581.80
  4985.9 1583.01  5003.0 1583.40  5006.6 1587.29  5013.2 1589.61  5035.2 1591.91
  5120.3 1590.90  5134.0 1590.04  5148.3 1591.51  5191.1 1590.76  5326.2 1594.24
  5574.4 1595.81  5603.0 1596.47  5609.5 1597.62  5681.0 1597.87  6012.5 1604.35
#Mann=4,-1,0
  4634.6    0.07       0  4947.7    0.07       0  4979.0    0.07       0
  5120.3   0.035       0
Bank Sta=4947.7,4979
Exp/Cntr=0.3,0.1

Type RM Length L Ch R = 1,34560,440,440,440
BEGIN DESCRIPTION:
Mapping XS c649f305
END DESCRIPTION:
XS GIS Cut Line= 3
      1674242.41      7002677.60      1674511.05      7002929.84
      1675067.12      7003518.67
#Sta/Elev= 30
  4631.5 1628.08  4640.7 1627.09  4683.1 1627.74  4718.3 1625.56  4725.6 1626.12
  4768.1 1622.10  4775.0 1620.22  4791.1 1618.49  4796.4 1618.11  4845.8 1606.83
  4930.8 1590.72  4937.6 1588.00  4959.1 1584.69  4973.3 1584.20  5002.2 1586.43
  5017.5 1589.77  5065.3 1591.52  5121.6 1590.56  5149.9 1588.07  5185.5 1586.99
  5205.0 1582.89  5205.5 1582.39  5236.3 1582.89  5242.1 1588.37  5263.2 1593.12
  5284.6 1591.40  5324.2 1591.41  5652.3 1592.60  5772.5 1594.39  5809.9 1593.85
#Mann=6,-1,0
  4631.5   0.035       0  4791.1    0.07       0  5017.5   0.035       0
  5205.0    0.07       0  5236.3   0.035       0  5324.2   0.035       0
Bank Sta=5205,5236.3
Exp/Cntr=0.3,0.1

Type RM Length L Ch R = 1,34120,474,474,474
BEGIN DESCRIPTION:
Mapping XS ca40fabc
END DESCRIPTION:
XS GIS Cut Line= 3
      1674024.50      7002921.41      1674304.92      7003267.97
      1675900.14      7004162.88
#Sta/Elev= 30
  4554.2 1614.70  4637.9 1616.61  4693.9 1614.28  4772.3 1592.45  4786.7 1589.77
  4819.4 1588.31  4984.9 1586.28  4996.8 1584.28  4998.1 1579.29  4998.6 1578.79
  5029.4 1579.29  5029.7 1581.07  5051.4 1582.80  5089.1 1580.37  5110.8 1584.20
  5116.5 1586.84  5132.4 1587.53  5148.4 1590.69  5231.9 1591.17  5699.5 1590.17
  5770.3 1593.85  6110.3 1601.03  6394.6 1609.96  6513.3 1613.99  6517.7 1614.11
  6580.4 1616.91  6642.1 1622.45  6720.0 1629.58  6791.5 1641.49  6829.1 1642.78
#Mann=10,-1,0
  4554.2    0.07       0  4819.4   0.035       0  4984.9    0.07       0
  4998.1    0.07       0  5029.4    0.07       0  5231.9   0.035       0
  6394.6    0.07       0  6513.3   0.035       0  6517.7    0.07       0
  6642.1   0.035       0
Bank Sta=4998.1,5029.4
Exp/Cntr=0.3,0.1

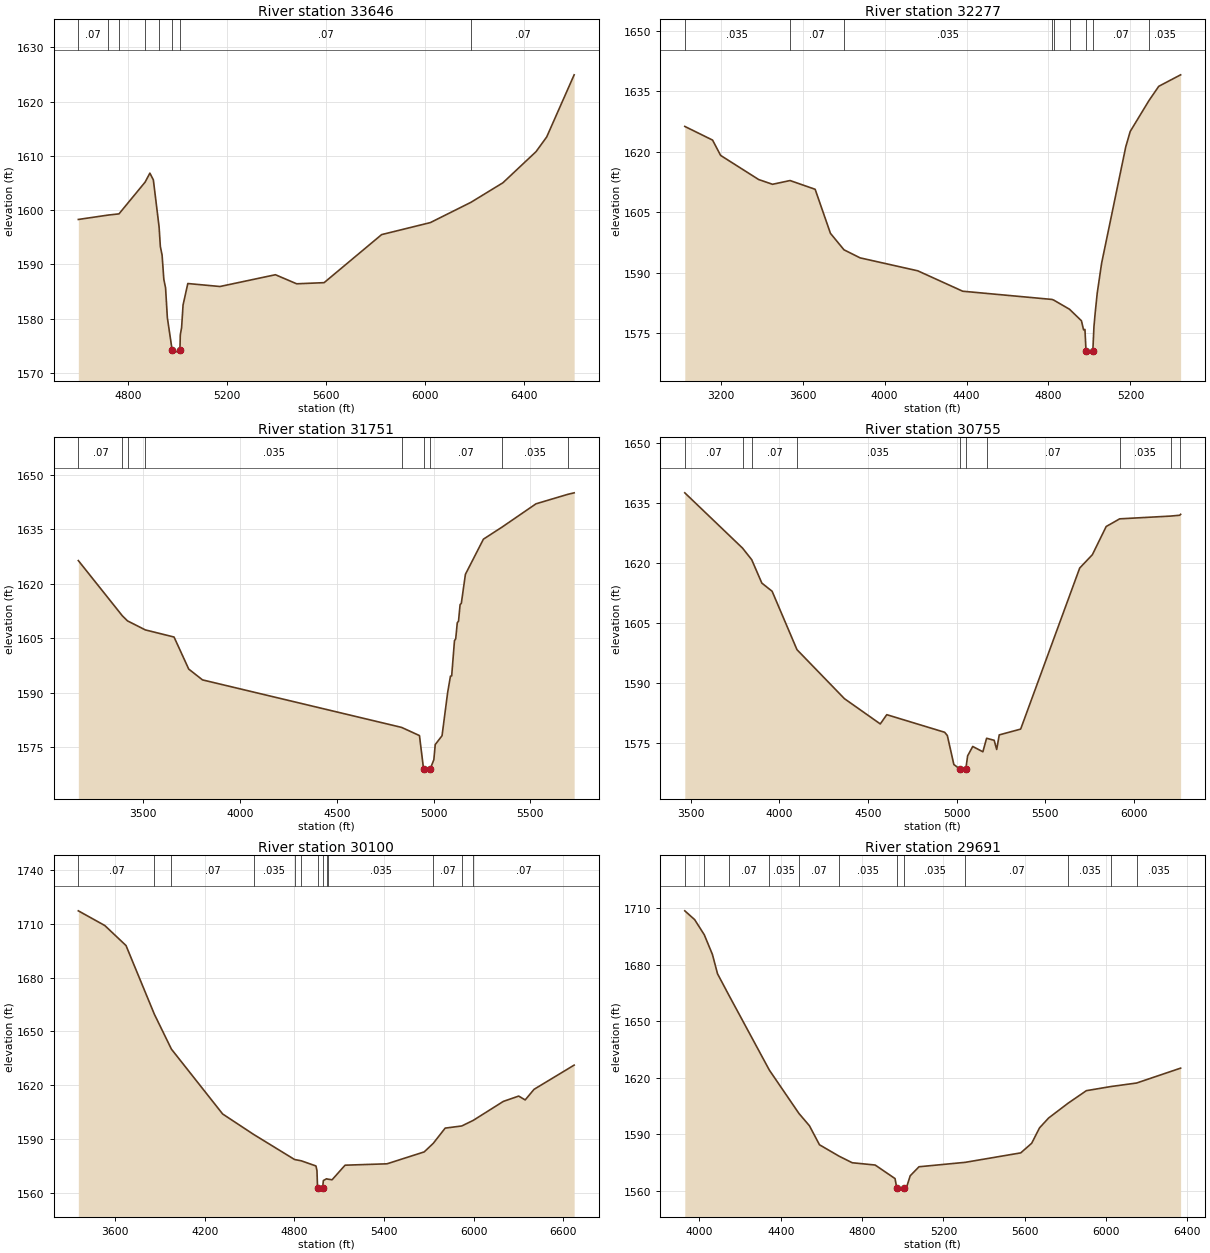
Type RM Length L Ch R = 1,33646,1369,1369,1369
BEGIN DESCRIPTION:
Mapping XS 2769dc22
END DESCRIPTION:
XS GIS Cut Line= 3
      1673816.64      7003387.14      1674104.69      7003667.70
      1675609.65      7004223.15
#Sta/Elev= 30
  4597.9 1598.27  4719.1 1599.08  4762.4 1599.30  4868.1 1605.15  4887.4 1606.81
  4901.5 1605.56  4924.7 1596.89  4929.8 1593.27  4936.8 1591.71  4943.9 1587.21
  4950.9 1585.67  4958.1 1580.17  4977.7 1574.13  4978.2 1573.63  5009.0 1574.13
  5010.5 1576.98  5015.8 1578.35  5021.7 1582.51  5040.9 1586.46  5170.9 1585.91
  5395.4 1588.08  5481.4 1586.41  5592.4 1586.62  5825.2 1595.48  6022.2 1597.69
  6186.6 1601.43  6315.9 1605.03  6450.0 1610.77  6493.1 1613.48  6604.2 1624.93
#Mann=8,-1,0
  4597.9    0.07       0  4719.1   0.035       0  4762.4    0.07       0
  4868.1   0.035       0  4924.7    0.07       0  4977.7   0.035       0
  5009.0    0.07       0  6186.6    0.07       0
Bank Sta=4977.7,5009
Exp/Cntr=0.3,0.1

Type RM Length L Ch R = 1,32277,526,526,526
BEGIN DESCRIPTION:
Mapping XS 83bd36e2
END DESCRIPTION:
XS GIS Cut Line= 3
      1673151.46      7002999.32      1674019.53      7004774.52
      1674240.44      7005160.03
#Sta/Elev= 30
  3024.7 1626.24  3160.2 1622.85  3199.6 1619.05  3385.3 1613.07  3452.9 1611.89
  3538.5 1612.82  3661.0 1610.65  3735.7 1599.73  3801.9 1595.64  3880.4 1593.65
  4161.9 1590.44  4381.3 1585.38  4817.5 1583.34  4826.0 1583.17  4902.7 1580.91
  4961.0 1578.05  4971.3 1575.80  4978.0 1575.90  4983.4 1570.53  4984.0 1570.03
  5016.5 1570.53  5022.0 1576.58  5027.8 1579.88  5037.8 1584.83  5059.4 1592.32
  5177.3 1621.18  5198.9 1624.98  5290.3 1632.63  5338.5 1636.19  5445.1 1639.03
#Mann=9,-1,0
  3024.7   0.035       0  3538.5    0.07       0  3801.9   0.035       0
  4817.5    0.07       0  4826.0   0.035       0  4902.7    0.07       0
  4983.4    0.07       0  5016.5    0.07       0  5290.3   0.035       0
Bank Sta=4983.4,5016.5
Exp/Cntr=0.3,0.1

Type RM Length L Ch R = 1,31751,996,996,996
BEGIN DESCRIPTION:
Mapping XS 43e869a9
END DESCRIPTION:
XS GIS Cut Line= 3
      1672664.49      7003325.74      1673549.91      7004945.53
      1673987.33      7005513.14
#Sta/Elev= 30
  3164.1 1626.40  3391.7 1611.20  3418.3 1609.81  3510.5 1607.33  3658.8 1605.37
  3734.7 1596.55  3805.8 1593.58  4834.8 1580.51  4927.2 1578.26  4948.6 1568.98
  4949.2 1568.48  4981.7 1568.98  5001.5 1571.61  5008.7 1575.79  5043.9 1578.22
  5072.9 1590.12  5087.4 1594.61  5093.7 1594.68  5108.2 1604.37  5114.5 1604.87
  5122.7 1609.32  5129.0 1609.71  5137.2 1614.29  5143.5 1614.63  5164.7 1622.62
  5257.7 1632.29  5355.1 1635.65  5529.5 1642.02  5694.2 1644.63  5726.7 1645.04
#Mann=9,-1,0
  3164.1    0.07       0  3391.7   0.035       0  3418.3    0.07       0
  3510.5   0.035       0  4834.8    0.07       0  4948.6    0.07       0
  4981.7    0.07       0  5355.1   0.035       0  5694.2    0.07       0
Bank Sta=4948.6,4981.7
Exp/Cntr=0.3,0.1

Type RM Length L Ch R = 1,30755,655,655,655
BEGIN DESCRIPTION:
Mapping XS 6f9510b4
END DESCRIPTION:
XS GIS Cut Line= 3
      1671792.52      7003591.77      1672599.82      7004899.09
      1673563.38      7005711.60
#Sta/Elev= 30
  3466.4 1637.43  3792.1 1623.62  3843.8 1620.73  3901.0 1614.88  3959.0 1612.84
  4099.2 1598.25  4366.9 1586.01  4569.1 1579.70  4605.7 1582.01  4932.0 1577.62
  4947.4 1576.80  4984.1 1569.57  5018.0 1568.41  5018.6 1567.91  5051.3 1568.41
  5062.0 1571.74  5090.6 1574.07  5147.8 1572.74  5168.8 1576.12  5211.5 1575.61
  5225.8 1573.32  5240.1 1576.96  5361.0 1578.41  5694.0 1618.64  5765.4 1621.97
  5843.5 1629.02  5919.5 1630.93  6206.4 1631.62  6258.3 1631.83  6263.3 1632.06
#Mann=10,-1,0
  3466.4    0.07       0  3792.1   0.035       0  3843.8    0.07       0
  4099.2   0.035       0  5018.0   0.035       0  5051.3   0.035       0
  5168.8    0.07       0  5919.5   0.035       0  6206.4    0.07       0
  6258.3   0.035       0
Bank Sta=5018,5051.3
Exp/Cntr=0.3,0.1

Type RM Length L Ch R = 1,30100,409,409,409
BEGIN DESCRIPTION:
Mapping XS 1c7cfc6a
END DESCRIPTION:
XS GIS Cut Line= 3
      1670743.93      7004029.30      1672014.75      7005091.80
      1673465.00      7005903.66
#Sta/Elev= 30
  3353.4 1717.08  3530.7 1708.90  3672.6 1697.77  3862.4 1659.55  3976.4 1640.17
  4319.3 1604.10  4527.3 1592.70  4800.4 1578.79  4845.8 1578.05  4943.9 1575.19
  4950.5 1572.65  4954.6 1562.81  4955.2 1562.31  4988.0 1562.81  4993.4 1567.09
  5015.1 1568.07  5022.8 1567.87  5051.8 1567.51  5138.6 1575.62  5419.4 1576.39
  5668.3 1583.01  5728.8 1587.76  5808.7 1596.24  5920.0 1597.44  5996.8 1600.56
  6198.0 1611.10  6300.7 1614.05  6344.1 1611.91  6403.5 1617.81  6671.9 1631.28
#Mann=13,-1,0
  3353.4    0.07       0  3862.4   0.035       0  3976.4    0.07       0
  4527.3   0.035       0  4800.4    0.07       0  4845.8   0.035       0
  4954.6   0.035       0  4988.0   0.035       0  5015.1    0.07       0
  5022.8   0.035       0  5728.8    0.07       0  5920.0   0.035       0
  5996.8    0.07       0
Bank Sta=4954.6,4988
Exp/Cntr=0.3,0.1

Type RM Length L Ch R = 1,29691,722,722,722
BEGIN DESCRIPTION:
Mapping XS e802db09
END DESCRIPTION:
XS GIS Cut Line= 3
      1670841.10      7005077.90      1671855.03      7005439.02
      1673118.94      7005945.97
#Sta/Elev= 30
  3928.1 1708.44  3976.6 1703.78  4023.8 1695.78  4063.7 1685.42  4089.2 1675.07
  4143.5 1664.04  4344.0 1624.06  4489.2 1601.15  4541.0 1594.60  4590.4 1584.53
  4688.0 1578.42  4751.5 1575.01  4864.2 1573.80  4961.9 1566.63  4970.7 1561.54
  4971.3 1561.04  5004.2 1561.54  5017.8 1561.81  5036.6 1568.12  5079.8 1572.89
  5307.1 1575.23  5580.0 1580.24  5633.8 1585.33  5672.4 1593.49  5717.2 1598.72
  5812.9 1606.55  5902.8 1613.19  6023.7 1615.38  6149.6 1617.23  6366.2 1625.12
#Mann=12,-1,0
  3928.1    0.07       0  4023.8   0.035       0  4143.5    0.07       0
  4344.0   0.035       0  4489.2    0.07       0  4688.0   0.035       0
  4970.7   0.035       0  5004.2   0.035       0  5307.1    0.07       0
  5812.9   0.035       0  6023.7    0.07       0  6149.6   0.035       0
Bank Sta=4970.7,5004.2
Exp/Cntr=0.3,0.1

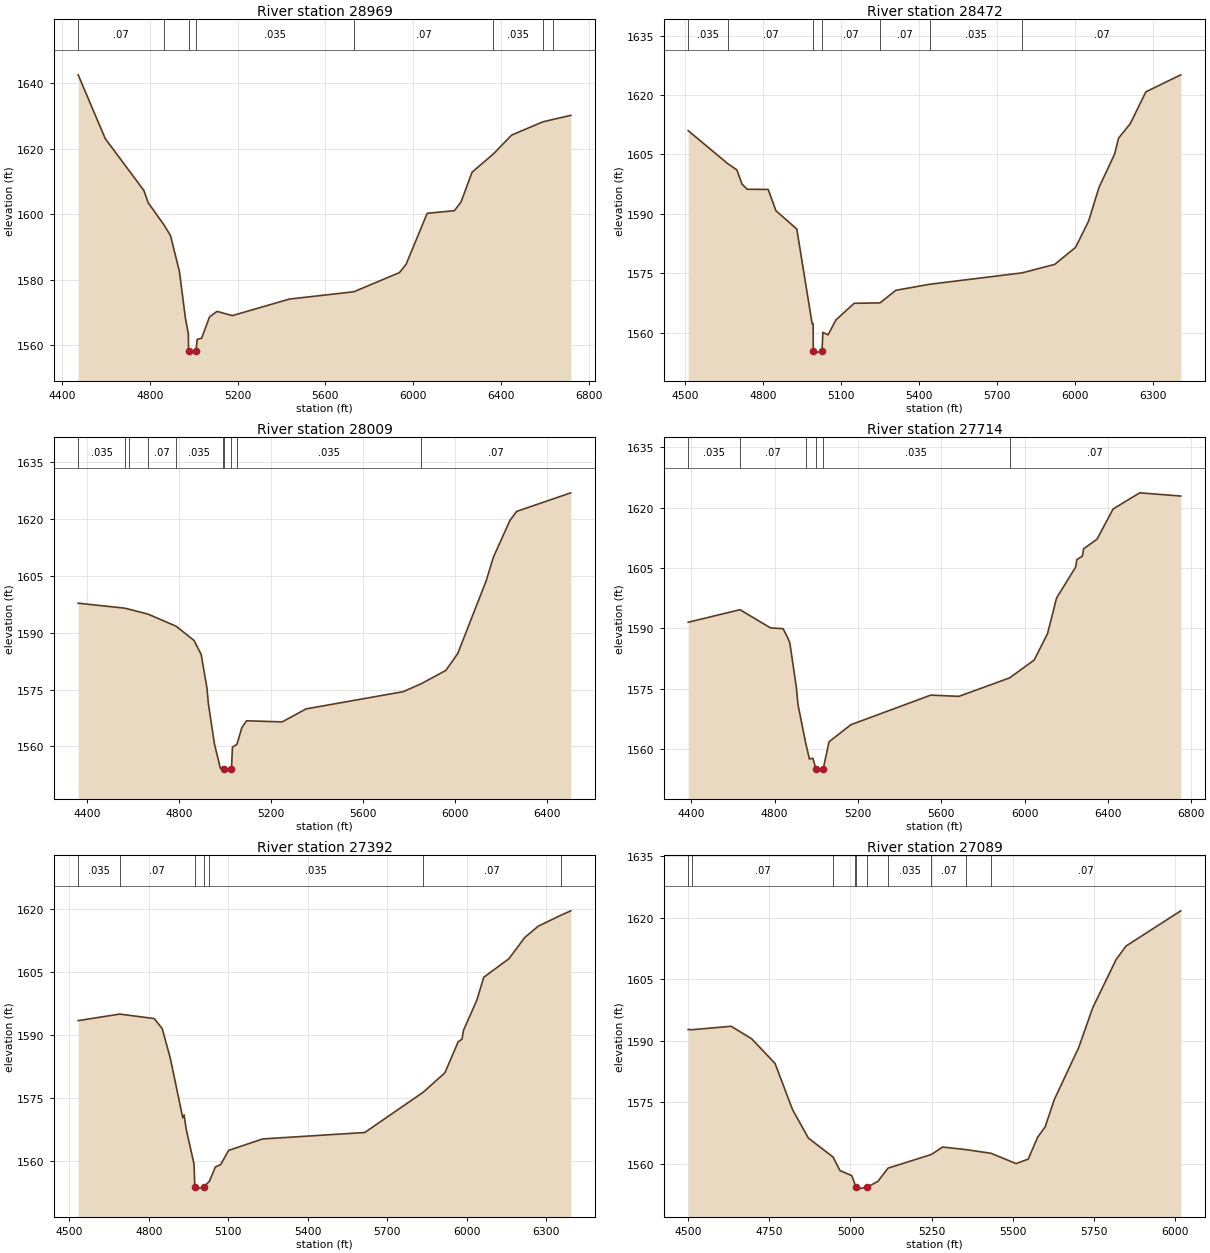
Type RM Length L Ch R = 1,28969,497,497,497
BEGIN DESCRIPTION:
Mapping XS e4935a84
END DESCRIPTION:
XS GIS Cut Line= 3
      1670889.79      7005902.42      1671405.38      7005988.35
      1673124.13      7006092.52
#Sta/Elev= 30
  4473.7 1642.49  4597.2 1623.04  4773.0 1607.25  4793.3 1603.45  4864.2 1596.80
  4894.6 1593.48  4935.2 1582.49  4962.2 1568.44  4975.7 1563.55  4976.9 1558.17
  4977.5 1557.67  5010.5 1558.17  5016.1 1561.86  5036.1 1562.22  5072.2 1568.69
  5106.2 1570.39  5176.3 1569.11  5436.8 1574.15  5729.8 1576.37  5937.7 1582.22
  5967.8 1584.73  6064.0 1600.28  6188.2 1601.09  6218.3 1603.74  6268.3 1612.80
  6365.4 1618.37  6448.7 1624.12  6590.9 1628.16  6635.3 1628.86  6718.3 1630.13
#Mann=8,-1,0
  4473.7    0.07       0  4864.2   0.035       0  4976.9   0.035       0
  5010.5   0.035       0  5729.8    0.07       0  6365.4   0.035       0
  6590.9    0.07       0  6635.3   0.035       0
Bank Sta=4976.9,5010.5
Exp/Cntr=0.3,0.1

Type RM Length L Ch R = 1,28472,463,463,463
BEGIN DESCRIPTION:
Mapping XS 9b8ea2b0
END DESCRIPTION:
XS GIS Cut Line= 3
      1670918.41      7006519.60      1671397.57      7006485.75
      1672808.99      7006410.23
#Sta/Elev= 30
  4512.3 1611.02  4663.5 1602.73  4699.4 1601.12  4719.4 1597.52  4739.5 1596.22
  4819.7 1596.19  4849.7 1590.82  4929.9 1586.18  4988.9 1562.30  4992.7 1562.30
  4993.3 1555.38  4993.9 1554.88  5026.9 1555.38  5030.1 1560.13  5050.2 1559.50
  5080.2 1563.25  5150.3 1567.45  5249.9 1567.56  5310.5 1570.73  5440.2 1572.25
  5795.3 1575.12  5921.4 1577.27  6001.5 1581.56  6051.6 1588.17  6091.7 1596.69
  6151.7 1605.10  6166.9 1609.12  6211.8 1612.77  6271.9 1620.81  6406.1 1625.10
#Mann=7,-1,0
  4512.3   0.035       0  4663.5    0.07       0  4993.3   0.035       0
  5026.9    0.07       0  5249.9    0.07       0  5440.2   0.035       0
  5795.3    0.07       0
Bank Sta=4993.3,5026.9
Exp/Cntr=0.3,0.1

Type RM Length L Ch R = 1,28009,295,295,295
BEGIN DESCRIPTION:
Mapping XS e920bb29
END DESCRIPTION:
XS GIS Cut Line= 3
      1670892.39      7007084.70      1671504.34      7006899.81
      1672961.37      7006525.15
#Sta/Elev= 30
  4360.0 1597.80  4563.0 1596.48  4582.5 1596.19  4664.2 1594.91  4786.6 1591.71
  4864.2 1587.96  4895.5 1584.24  4920.4 1575.42  4926.8 1571.21  4953.3 1560.58
  4979.1 1554.14  4988.6 1554.48  4993.4 1553.97  4994.1 1553.47  5027.1 1553.97
  5031.4 1559.82  5050.8 1560.53  5072.2 1564.93  5092.9 1566.76  5247.8 1566.47
  5352.0 1569.90  5774.3 1574.44  5852.6 1576.53  5960.2 1580.06  6011.8 1584.51
  6135.7 1603.74  6166.7 1609.91  6239.0 1619.65  6268.1 1622.02  6503.7 1626.93
#Mann=10,-1,0
  4360.0   0.035       0  4563.0    0.07       0  4582.5   0.035       0
  4664.2    0.07       0  4786.6   0.035       0  4988.6    0.07       0
  4993.4    0.07       0  5027.1    0.07       0  5050.8   0.035       0
  5852.6    0.07       0
Bank Sta=4993.4,5027.1
Exp/Cntr=0.3,0.1

Type RM Length L Ch R = 1,27714,322,322,322
BEGIN DESCRIPTION:
Mapping XS 45f3f76a
END DESCRIPTION:
XS GIS Cut Line= 3
      1670967.92      7007355.53      1671556.42      7007178.46
      1673224.78      7006652.71
#Sta/Elev= 30
  4385.3 1591.50  4634.0 1594.61  4780.1 1590.10  4840.9 1589.89  4862.6 1587.67
  4873.1 1586.36  4904.4 1575.32  4912.2 1571.04  4948.9 1561.53  4967.1 1557.50
  4983.4 1557.69  4999.1 1554.98  4999.8 1554.48  5033.0 1554.98  5061.3 1561.78
  5166.1 1566.02  5549.6 1573.38  5684.3 1573.07  5927.2 1577.65  6045.5 1582.09
  6109.8 1588.67  6153.1 1597.53  6244.9 1605.24  6250.2 1607.05  6277.3 1607.95
  6282.5 1609.73  6347.3 1612.15  6424.3 1619.65  6551.9 1623.67  6749.1 1622.87
#Mann=6,-1,0
  4385.3   0.035       0  4634.0    0.07       0  4948.9   0.035       0
  4999.1   0.035       0  5033.0   0.035       0  5927.2    0.07       0
Bank Sta=4999.1,5033
Exp/Cntr=0.3,0.1

Type RM Length L Ch R = 1,27392,303,303,303
BEGIN DESCRIPTION:
Mapping XS 84430e10
END DESCRIPTION:
XS GIS Cut Line= 3
      1671137.98      7007470.12      1671606.77      7007485.32
      1672986.95      7007652.41
#Sta/Elev= 30
  4533.1 1593.47  4689.9 1595.03  4820.3 1593.96  4850.3 1591.56  4880.3 1584.66
  4928.0 1570.26  4933.0 1570.98  4940.3 1567.75  4970.4 1559.23  4973.4 1553.76
  4974.1 1553.26  5007.3 1553.76  5028.6 1555.14  5050.7 1558.53  5071.0 1559.12
  5101.1 1562.51  5229.7 1565.24  5614.8 1566.77  5835.7 1576.40  5917.0 1581.00
  5967.4 1588.40  5981.9 1589.05  5987.5 1591.16  6037.9 1598.36  6063.8 1603.81
  6158.8 1608.23  6219.2 1613.34  6269.6 1616.00  6353.6 1618.58  6392.4 1619.67
#Mann=7,-1,0
  4533.1   0.035       0  4689.9    0.07       0  4973.4    0.07       0
  5007.3    0.07       0  5028.6   0.035       0  5835.7    0.07       0
  6353.6   0.035       0
Bank Sta=4973.4,5007.3
Exp/Cntr=0.3,0.1

Type RM Length L Ch R = 1,27089,814,814,814
BEGIN DESCRIPTION:
Mapping XS 67a5f7d0
END DESCRIPTION:
XS GIS Cut Line= 3
      1671178.38      7007622.03      1671652.34      7007770.47
      1672537.78      7008275.69
#Sta/Elev= 30
  4500.6 1592.77  4512.3 1592.72  4632.9 1593.56  4696.2 1590.50  4767.9 1584.51
  4821.9 1573.25  4870.5 1566.34  4946.6 1561.71  4967.8 1558.42  5004.2 1557.19
  5014.8 1554.89  5017.9 1554.40  5018.6 1553.90  5051.9 1554.40  5084.9 1555.81
  5115.5 1559.00  5249.1 1562.34  5283.6 1564.15  5355.0 1563.53  5432.6 1562.63
  5509.7 1560.12  5547.2 1561.21  5576.0 1566.53  5599.0 1569.02  5627.8 1575.77
  5702.6 1588.39  5745.9 1598.11  5817.8 1609.83  5848.2 1613.10  6016.7 1621.67
#Mann=10,-1,0
  4500.6   0.035       0  4512.3    0.07       0  4946.6   0.035       0
  5014.8    0.07       0  5017.9   0.035       0  5051.9    0.07       0
  5115.5   0.035       0  5249.1    0.07       0  5355.0   0.035       0
  5432.6    0.07       0
Bank Sta=5017.9,5051.9
Exp/Cntr=0.3,0.1

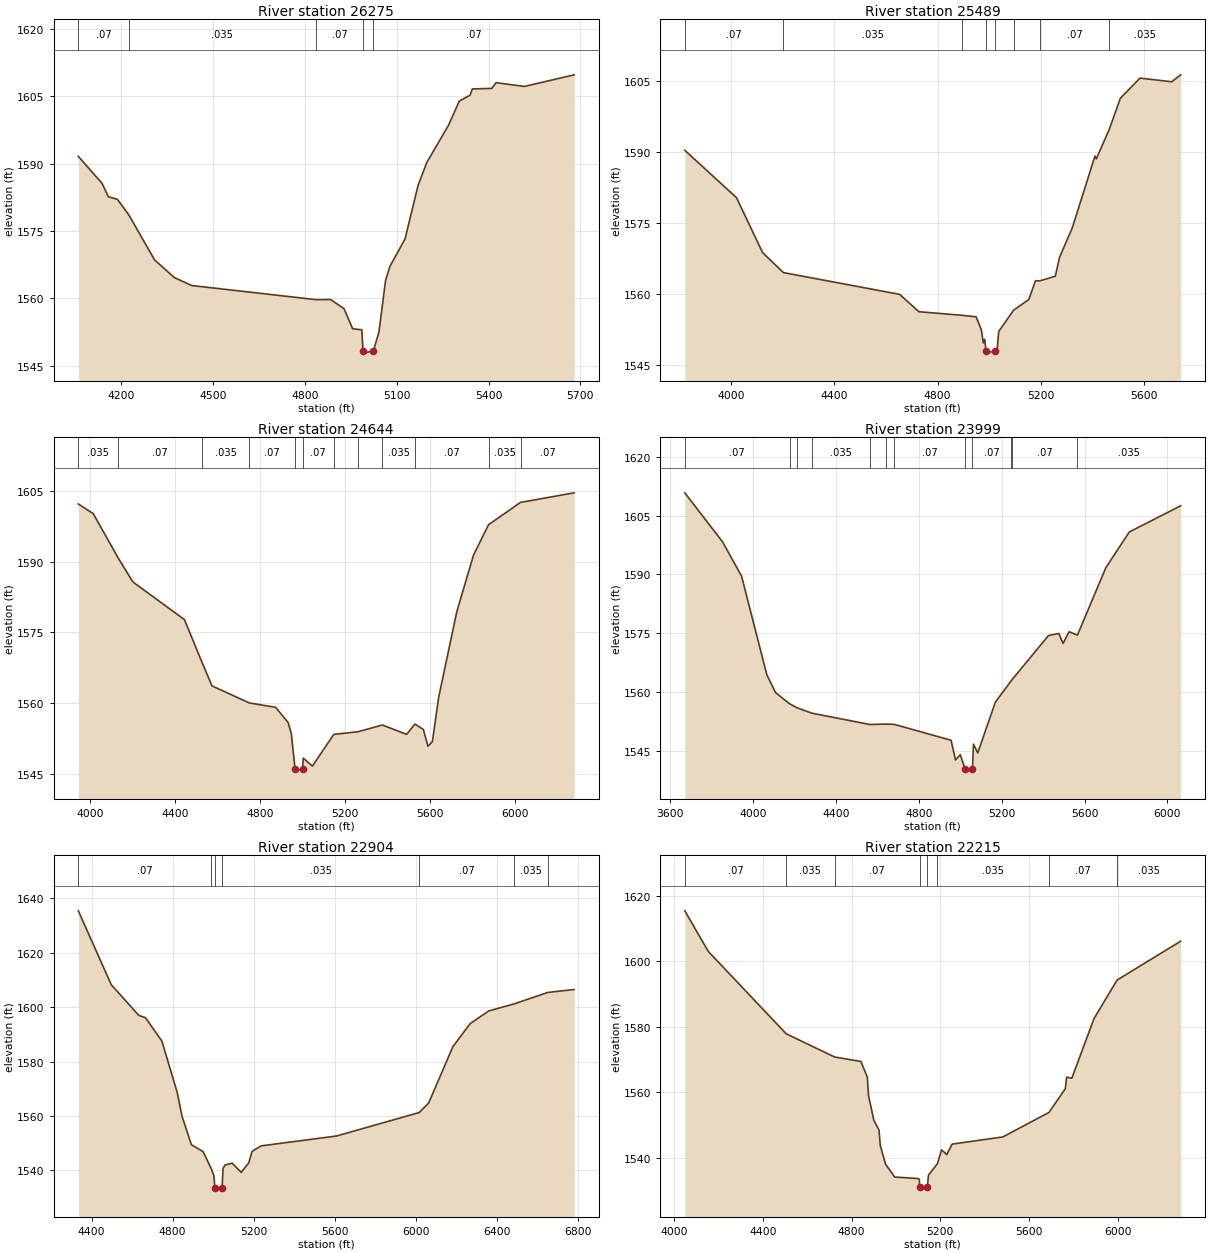
Type RM Length L Ch R = 1,26275,786,786,786
BEGIN DESCRIPTION:
Mapping XS 62a62988
END DESCRIPTION:
XS GIS Cut Line= 3
      1671223.93      7007712.85      1671757.81      7008489.80
      1672259.21      7008943.65
#Sta/Elev= 30
  4060.6 1591.60  4137.8 1585.63  4158.7 1582.62  4188.2 1582.05  4225.5 1578.58
  4309.5 1568.58  4373.9 1564.65  4430.8 1562.87  4836.4 1559.73  4884.7 1559.75
  4928.3 1557.71  4956.4 1553.25  4986.2 1553.02  4990.2 1548.33  4990.8 1547.83
  5024.2 1548.33  5042.3 1552.56  5063.9 1564.04  5078.1 1567.14  5127.5 1573.26
  5170.0 1585.16  5198.4 1590.25  5269.3 1598.52  5304.5 1603.90  5339.7 1605.22
  5347.1 1606.61  5410.7 1606.73  5424.8 1608.01  5516.8 1607.16  5679.6 1609.75
#Mann=5,-1,0
  4060.6    0.07       0  4225.5   0.035       0  4836.4    0.07       0
  4990.2    0.07       0  5024.2    0.07       0
Bank Sta=4990.2,5024.2
Exp/Cntr=0.3,0.1

Type RM Length L Ch R = 1,25489,845,845,845
BEGIN DESCRIPTION:
Mapping XS 074775d8
END DESCRIPTION:
XS GIS Cut Line= 3
      1671067.70      7007719.40      1671213.10      7008893.45
      1671369.35      7009611.73
#Sta/Elev= 30
  3822.4 1590.34  4022.5 1580.35  4123.3 1568.79  4203.8 1564.57  4653.5 1559.98
  4727.9 1556.33  4894.9 1555.57  4949.5 1555.25  4969.7 1552.49  4977.4 1549.74
  4982.5 1550.52  4987.7 1548.10  4988.5 1547.60  5022.6 1548.10  5030.5 1548.26
  5036.8 1552.17  5094.7 1556.67  5153.3 1558.90  5179.0 1562.86  5195.5 1562.82
  5255.7 1563.81  5272.1 1567.77  5321.2 1573.97  5409.2 1589.12  5414.3 1588.53
  5463.5 1594.61  5507.4 1601.30  5583.2 1605.55  5706.0 1604.78  5740.5 1606.24
#Mann=8,-1,0
  3822.4    0.07       0  4203.8   0.035       0  4894.9    0.07       0
  4987.7    0.07       0  5022.6    0.07       0  5094.7   0.035       0
  5195.5    0.07       0  5463.5   0.035       0
Bank Sta=4987.7,5022.6
Exp/Cntr=0.3,0.1

Type RM Length L Ch R = 1,24644,645,645,645
BEGIN DESCRIPTION:
Mapping XS 5ac945de
END DESCRIPTION:
XS GIS Cut Line= 3
      1669838.96      7007786.23      1670461.37      7008645.62
      1671216.57      7009669.04
#Sta/Elev= 30
  3944.6 1602.21  4014.6 1600.17  4131.4 1590.81  4201.0 1585.68  4443.8 1577.68
  4525.8 1568.69  4573.7 1563.61  4749.2 1559.99  4873.0 1559.06  4931.8 1555.84
  4946.5 1553.54  4964.4 1546.02  4965.2 1545.52  4999.6 1546.02  5002.9 1548.28
  5045.9 1546.59  5146.7 1553.32  5259.4 1553.87  5375.4 1555.30  5489.5 1553.32
  5528.4 1555.52  5567.9 1554.37  5589.7 1550.81  5610.6 1551.78  5639.8 1561.12
  5725.4 1579.36  5804.0 1591.35  5874.6 1597.81  6025.3 1602.55  6277.6 1604.58
#Mann=12,-1,0
  3944.6   0.035       0  4131.4    0.07       0  4525.8   0.035       0
  4749.2    0.07       0  4964.4    0.07       0  4999.6    0.07       0
  5146.7   0.035       0  5259.4    0.07       0  5375.4   0.035       0
  5528.4    0.07       0  5874.6   0.035       0  6025.3    0.07       0
Bank Sta=4964.4,4999.6
Exp/Cntr=0.3,0.1

Type RM Length L Ch R = 1,23999,1095,1095,1095
BEGIN DESCRIPTION:
Mapping XS bf857fb9
END DESCRIPTION:
XS GIS Cut Line= 3
      1669471.79      7008119.58      1670240.01      7009210.72
      1670910.94      7010029.88
#Sta/Elev= 30
  3670.3 1610.77  3851.8 1598.36  3944.3 1589.59  4066.3 1564.47  4108.6 1559.94
  4175.9 1557.12  4211.3 1556.11  4283.8 1554.72  4563.8 1551.84  4641.5 1551.95
  4681.4 1551.87  4955.6 1547.83  4977.0 1542.83  5000.0 1544.16  5023.8 1540.48
  5024.5 1539.98  5059.0 1540.48  5063.6 1546.84  5084.4 1544.61  5169.3 1557.52
  5245.6 1562.94  5250.3 1563.27  5426.1 1574.48  5475.6 1574.99  5496.4 1572.46
  5525.1 1575.43  5565.6 1574.58  5702.4 1591.70  5815.8 1600.81  6063.6 1607.47
#Mann=12,-1,0
  3670.3    0.07       0  4175.9   0.035       0  4211.3    0.07       0
  4283.8   0.035       0  4563.8    0.07       0  4641.5   0.035       0
  4681.4    0.07       0  5023.8    0.07       0  5059.0    0.07       0
  5245.6   0.035       0  5250.3    0.07       0  5565.6   0.035       0
Bank Sta=5023.8,5059
Exp/Cntr=0.3,0.1

Type RM Length L Ch R = 1,22904,689,689,689
BEGIN DESCRIPTION:
Mapping XS dc4c9712
END DESCRIPTION:
XS GIS Cut Line= 4
      1669084.56      7008234.37      1669355.38      7008852.39
      1669660.93      7009453.08      1670410.50      7010258.17
#Sta/Elev= 30
  4334.4 1635.31  4497.1 1608.18  4633.2 1596.92  4665.9 1596.08  4747.2 1587.48
  4822.8 1568.63  4846.2 1560.00  4892.9 1549.43  4950.6 1546.94  4991.0 1540.67
  5004.0 1538.09  5009.0 1533.66  5009.8 1533.16  5044.3 1533.66  5049.1 1540.77
  5059.1 1542.03  5094.0 1542.68  5138.9 1539.31  5175.9 1542.77  5192.6 1547.04
  5237.1 1549.04  5609.7 1552.66  6017.9 1561.27  6064.4 1564.75  6184.6 1585.50
  6269.6 1593.91  6361.5 1598.57  6485.4 1601.12  6652.9 1605.35  6783.1 1606.43
#Mann=7,-1,0
  4334.4    0.07       0  4991.0   0.035       0  5009.0   0.035       0
  5044.3   0.035       0  6017.9    0.07       0  6485.4   0.035       0
  6652.9    0.07       0
Bank Sta=5009,5044.3
Exp/Cntr=0.3,0.1

Type RM Length L Ch R = 1,22215,831,831,831
BEGIN DESCRIPTION:
Mapping XS 18eaea9b
END DESCRIPTION:
XS GIS Cut Line= 3
      1668657.48      7008487.85      1669032.46      7009369.75
      1669532.38      7010543.18
#Sta/Elev= 30
  4048.7 1615.42  4154.7 1603.02  4505.5 1577.89  4723.4 1570.81  4842.0 1569.44
  4871.1 1564.64  4876.5 1559.02  4900.2 1551.54  4923.8 1548.48  4929.3 1543.84
  4952.9 1538.13  4994.2 1534.16  5100.1 1533.70  5105.6 1533.41  5106.1 1530.97
  5106.9 1530.47  5141.5 1530.97  5146.4 1534.72  5186.3 1538.16  5205.5 1542.46
  5229.1 1541.01  5252.8 1544.21  5481.7 1546.40  5689.8 1553.90  5763.3 1561.17
  5768.8 1564.64  5792.4 1564.33  5892.4 1582.54  5996.3 1594.29  6282.5 1606.14
#Mann=8,-1,0
  4048.7    0.07       0  4505.5   0.035       0  4723.4    0.07       0
  5106.1    0.07       0  5141.5    0.07       0  5186.3   0.035       0
  5689.8    0.07       0  5996.3   0.035       0
Bank Sta=5106.1,5141.5
Exp/Cntr=0.3,0.1

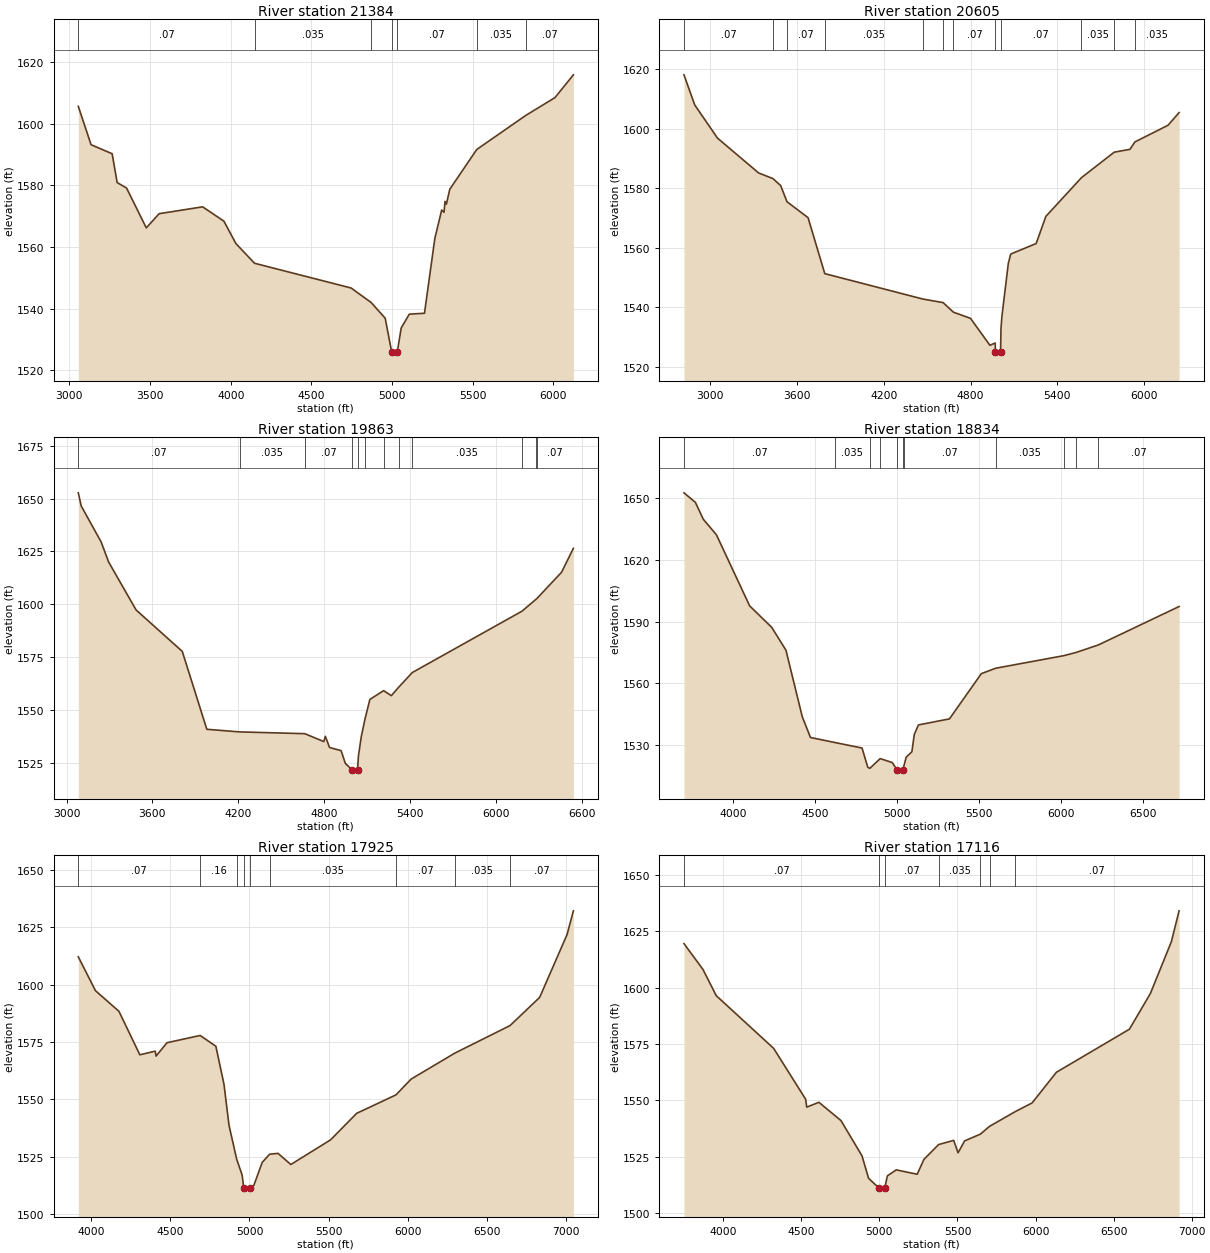
Type RM Length L Ch R = 1,21384,779,779,779
BEGIN DESCRIPTION:
Mapping XS da05a281
END DESCRIPTION:
XS GIS Cut Line= 3
      1667713.38      7008410.27      1668720.32      7010076.92
      1669384.37      7010979.68
#Sta/Elev= 30
  3055.7 1605.67  3134.8 1593.21  3265.5 1590.28  3296.6 1580.93  3354.8 1579.16
  3477.0 1566.24  3556.6 1570.84  3826.3 1573.07  3958.3 1568.40  4032.0 1561.18
  4147.8 1554.77  4746.1 1546.75  4869.6 1542.08  4957.4 1536.95  4997.1 1526.13
  4997.9 1525.63  5032.6 1526.13  5056.6 1533.80  5106.7 1538.26  5200.8 1538.56
  5264.9 1562.77  5307.3 1572.03  5321.9 1571.30  5328.1 1574.83  5336.6 1573.93
  5357.4 1578.76  5524.7 1591.66  5828.2 1602.70  6009.3 1608.48  6123.6 1615.87
#Mann=7,-1,0
  3055.7    0.07       0  4147.8   0.035       0  4869.6    0.07       0
  4997.1    0.07       0  5032.6    0.07       0  5524.7   0.035       0
  5828.2    0.07       0
Bank Sta=4997.1,5032.6
Exp/Cntr=0.3,0.1

Type RM Length L Ch R = 1,20605,742,742,742
BEGIN DESCRIPTION:
Mapping XS 2d77e53a
END DESCRIPTION:
XS GIS Cut Line= 3
      1667487.69      7008518.78      1668182.13      7010593.42
      1667978.14      7011813.00
#Sta/Elev= 30
  2817.7 1618.18  2892.0 1608.06  3049.8 1596.88  3334.0 1585.17  3432.5 1583.29
  3486.5 1580.94  3530.1 1575.50  3676.0 1570.12  3791.5 1551.31  4469.3 1542.77
  4609.9 1541.56  4681.4 1538.34  4799.4 1536.27  4933.5 1527.22  4970.3 1527.97
  4971.2 1525.07  4972.1 1524.57  5007.2 1525.07  5010.3 1532.95  5016.8 1537.01
  5060.8 1554.72  5077.5 1557.90  5253.5 1561.43  5320.4 1570.55  5566.6 1583.58
  5793.7 1592.17  5902.3 1593.12  5936.2 1595.60  6165.5 1601.22  6242.0 1605.48
#Mann=12,-1,0
  2817.7    0.07       0  3432.5   0.035       0  3530.1    0.07       0
  3791.5   0.035       0  4469.3    0.07       0  4609.9   0.035       0
  4681.4    0.07       0  4971.2    0.07       0  5007.2    0.07       0
  5566.6   0.035       0  5793.7    0.07       0  5936.2   0.035       0
Bank Sta=4971.2,5007.2
Exp/Cntr=0.3,0.1

Type RM Length L Ch R = 1,19863,1029,1029,1029
BEGIN DESCRIPTION:
Mapping XS b40c52b0
END DESCRIPTION:
XS GIS Cut Line= 3
      1667228.13      7008537.85      1667488.55      7010454.53
      1667493.76      7011980.53
#Sta/Elev= 30
  3082.2 1652.69  3102.5 1646.50  3241.7 1629.50  3294.3 1619.99  3486.0 1597.35
  3809.0 1577.75  3980.5 1540.94  4209.0 1539.71  4665.2 1538.87  4798.0 1535.14
  4808.8 1537.62  4838.3 1532.33  4919.1 1530.85  4948.6 1524.81  4997.7 1521.67
  4998.6 1521.17  5033.7 1521.67  5040.0 1528.26  5060.0 1537.52  5086.7 1545.99
  5120.0 1555.05  5216.1 1559.20  5270.0 1556.83  5320.2 1560.73  5416.2 1567.75
  6183.3 1596.76  6277.6 1602.18  6289.3 1602.88  6460.0 1615.18  6542.5 1626.48
#Mann=12,-1,0
  3082.2    0.07       0  4209.0   0.035       0  4665.2    0.07       0
  4997.7    0.07       0  5033.7    0.07       0  5086.7    0.07       0
  5216.1   0.035       0  5320.2    0.07       0  5416.2   0.035       0
  6183.3    0.07       0  6277.6   0.035       0  6289.3    0.07       0
Bank Sta=4997.7,5033.7
Exp/Cntr=0.3,0.1

Type RM Length L Ch R = 1,18834,909,909,909
BEGIN DESCRIPTION:
Mapping XS 7b1f86de
END DESCRIPTION:
XS GIS Cut Line= 3
      1666991.16      7008681.07      1666648.27      7009957.13
      1666205.58      7011597.72
#Sta/Elev= 30
  3699.5 1652.63  3768.8 1648.03  3817.5 1639.78  3897.4 1632.25  4100.2 1597.67
  4234.8 1587.25  4321.7 1576.13  4421.2 1543.79  4471.2 1533.70  4619.8 1531.27
  4785.9 1528.58  4820.7 1519.25  4833.5 1518.71  4896.5 1523.44  4970.0 1521.53
  5000.6 1517.85  5001.4 1517.35  5036.8 1517.85  5039.1 1519.21  5055.3 1524.17
  5090.0 1526.77  5104.6 1535.19  5129.9 1539.81  5319.1 1542.74  5513.5 1564.72
  5600.8 1567.36  6016.5 1573.47  6089.1 1574.97  6228.0 1578.70  6720.1 1597.37
#Mann=11,-1,0
  3699.5    0.07       0  4619.8   0.035       0  4833.5    0.07       0
  4896.5   0.035       0  5000.6   0.035       0  5036.8   0.035       0
  5039.1    0.07       0  5600.8   0.035       0  6016.5    0.07       0
  6089.1   0.035       0  6228.0    0.07       0
Bank Sta=5000.6,5036.8
Exp/Cntr=0.3,0.1

Type RM Length L Ch R = 1,17925,809,809,809
BEGIN DESCRIPTION:
Mapping XS e2433cb1
END DESCRIPTION:
XS GIS Cut Line= 3
      1666465.99      7008355.56      1666005.91      7009345.15
      1665138.43      7011184.21
#Sta/Elev= 30
  3919.8 1612.04  4028.1 1597.32  4176.4 1588.34  4308.2 1569.43  4405.3 1571.02
  4410.8 1568.87  4479.5 1574.68  4688.9 1577.83  4788.1 1573.14  4839.3 1556.60
  4870.9 1538.82  4919.4 1524.03  4953.8 1517.12  4964.0 1511.51  4964.8 1511.01
  5000.4 1511.51  5027.9 1512.67  5080.6 1522.65  5126.9 1526.18  5180.1 1526.57
  5261.2 1521.72  5511.7 1532.43  5676.7 1543.97  5925.0 1552.01  6020.4 1558.87
  6295.7 1570.14  6644.5 1582.13  6831.5 1594.39  7004.5 1621.73  7044.5 1632.04
#Mann=9,-1,0
  3919.8    0.07       0  4688.9    0.16       0  4919.4    0.07       0
  4964.0    0.07       0  5000.4    0.07       0  5126.9   0.035       0
  5925.0    0.07       0  6295.7   0.035       0  6644.5    0.07       0
Bank Sta=4964,5000.4
Exp/Cntr=0.3,0.1

Type RM Length L Ch R = 1,17116,657,657,657
BEGIN DESCRIPTION:
Mapping XS a52679a9
END DESCRIPTION:
XS GIS Cut Line= 3
      1666140.66      7008241.44      1665250.05      7009152.88
      1663969.81      7010552.83
#Sta/Elev= 30
  3748.3 1619.44  3870.0 1608.00  3954.9 1596.40  4322.7 1573.04  4527.7 1550.51
  4534.8 1547.01  4612.5 1549.15  4754.0 1541.05  4888.5 1525.44  4930.9 1515.46
  4997.4 1511.18  4998.3 1510.68  5034.1 1511.18  5051.1 1516.55  5107.9 1519.21
  5242.3 1517.27  5284.8 1523.81  5379.3 1530.43  5476.0 1532.28  5503.9 1526.77
  5546.3 1532.07  5646.9 1535.04  5705.7 1538.50  5871.5 1545.07  5978.1 1548.86
  6134.0 1562.46  6601.5 1581.52  6735.9 1597.35  6870.3 1620.32  6919.7 1633.97
#Mann=7,-1,0
  3748.3    0.07       0  4997.4    0.07       0  5034.1    0.07       0
  5379.3   0.035       0  5646.9    0.07       0  5705.7   0.035       0
  5871.5    0.07       0
Bank Sta=4997.4,5034.1
Exp/Cntr=0.3,0.1