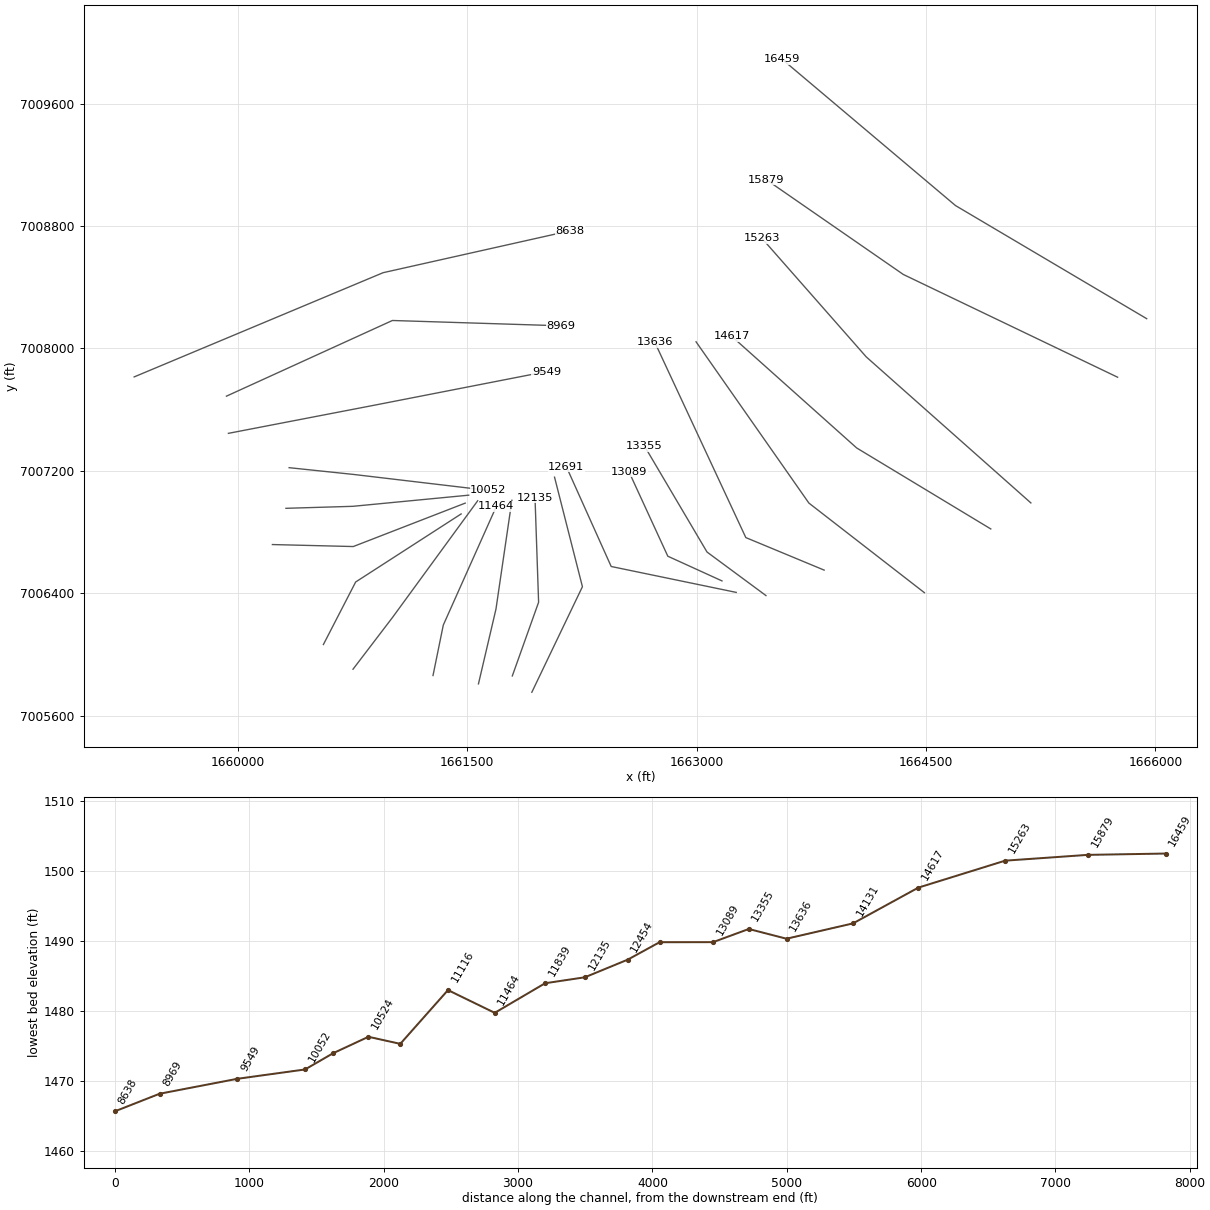
HEC-RAS study Fish Creek.prj: Fish Creek Base Level Engineering

--- Fish Creek.g01 (geometry) --- (continued)

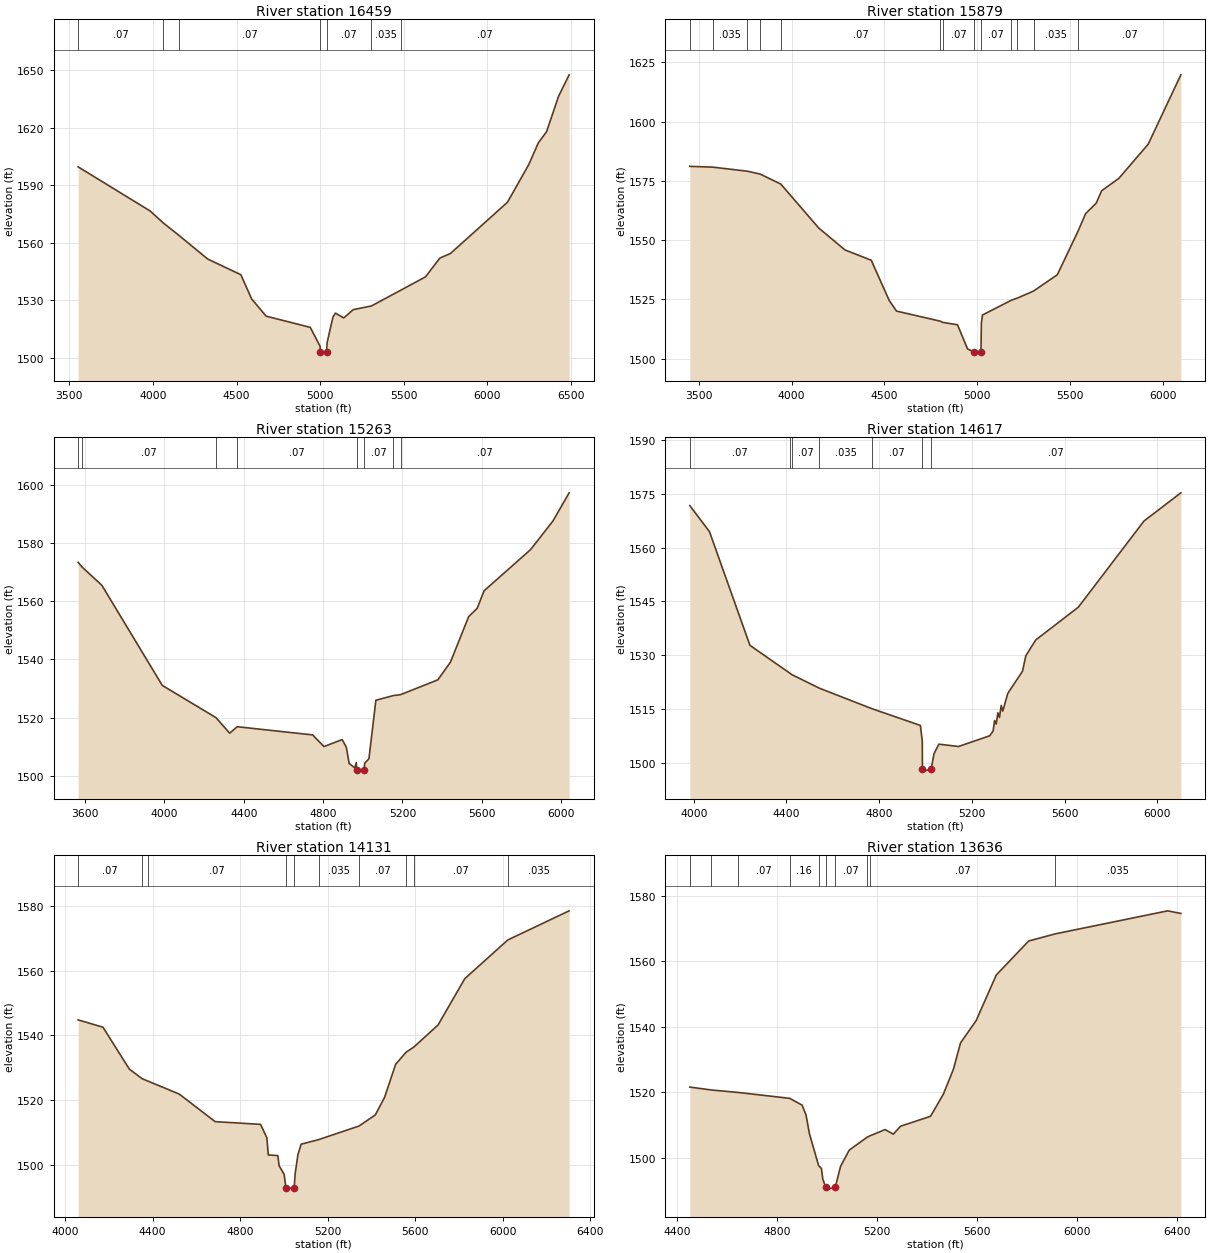
Type RM Length L Ch R = 1,16459,580,580,580
BEGIN DESCRIPTION:
Mapping XS c02a8749
END DESCRIPTION:
XS GIS Cut Line= 3
      1665942.78      7008194.54      1664692.76      7008934.13
      1663558.66      7009891.36
#Sta/Elev= 30
  3551.9 1599.57  3983.0 1576.57  4061.5 1570.34  4152.6 1564.06  4327.8 1551.50
  4525.2 1543.40  4589.5 1530.83  4676.4 1521.81  4940.5 1515.96  4999.0 1506.15
  5001.2 1503.05  5002.1 1502.55  5038.0 1503.05  5040.7 1507.84  5062.4 1516.17
  5076.7 1521.46  5091.0 1523.37  5140.5 1520.88  5197.6 1525.19  5306.1 1527.12
  5482.9 1535.38  5629.5 1542.27  5715.2 1552.04  5778.9 1554.45  6119.5 1581.12
  6247.0 1600.73  6304.2 1612.06  6353.6 1617.89  6425.1 1636.30  6488.4 1647.49
#Mann=7,-1,0
  3551.9    0.07       0  4061.5    0.16       0  4152.6    0.07       0
  5001.2    0.07       0  5038.0    0.07       0  5306.1   0.035       0
  5482.9    0.07       0
Bank Sta=5001.2,5038
Exp/Cntr=0.3,0.1

Type RM Length L Ch R = 1,15879,616,616,616
BEGIN DESCRIPTION:
Mapping XS ad848e4a
END DESCRIPTION:
XS GIS Cut Line= 3
      1665752.63      7007811.75      1664351.62      7008483.61
      1663456.04      7009103.22
#Sta/Elev= 30
  3452.5 1581.15  3575.7 1580.82  3761.8 1579.11  3831.0 1577.90  3942.4 1573.66
  4146.1 1555.15  4287.6 1545.89  4429.0 1541.54  4525.6 1524.59  4565.0 1520.09
  4799.6 1515.86  4813.0 1515.34  4893.2 1514.33  4947.1 1504.14  4982.5 1502.86
  4983.4 1502.36  5019.4 1502.86  5021.6 1515.05  5027.7 1518.45  5183.6 1524.69
  5215.9 1525.60  5302.3 1528.54  5430.4 1535.42  5540.6 1553.57  5582.5 1561.19
  5639.3 1565.58  5669.0 1570.86  5761.6 1576.09  5919.7 1590.53  6095.3 1619.76
#Mann=13,-1,0
  3452.5    0.07       0  3575.7   0.035       0  3761.8    0.07       0
  3831.0    0.16       0  3942.4    0.07       0  4799.6    0.16       0
  4813.0    0.07       0  4982.5    0.07       0  5019.4    0.07       0
  5183.6   0.035       0  5215.9    0.07       0  5302.3   0.035       0
  5540.6    0.07       0
Bank Sta=4982.5,5019.4
Exp/Cntr=0.3,0.1

Type RM Length L Ch R = 1,15263,646,646,646
BEGIN DESCRIPTION:
Mapping XS cf86985e
END DESCRIPTION:
XS GIS Cut Line= 3
      1665185.66      7006989.84      1664109.26      7007944.72
      1663425.21      7008722.51
#Sta/Elev= 30
  3565.1 1573.49  3584.0 1571.94  3685.0 1565.55  3989.4 1531.07  4260.3 1519.95
  4329.0 1514.60  4366.9 1516.83  4747.1 1514.01  4804.0 1510.00  4896.0 1512.39
  4916.9 1509.81  4931.1 1504.18  4959.6 1502.66  4967.1 1504.49  4969.5 1502.03
  4970.4 1501.53  5006.5 1502.03  5009.5 1504.27  5030.8 1505.78  5065.9 1525.95
  5154.2 1527.57  5190.5 1527.88  5378.0 1532.98  5441.6 1539.06  5533.6 1554.78
  5576.3 1557.62  5611.4 1563.68  5845.8 1577.87  5958.7 1587.76  6039.8 1597.42
#Mann=8,-1,0
  3565.1    0.16       0  3584.0    0.07       0  4260.3   0.035       0
  4366.9    0.07       0  4969.5    0.07       0  5006.5    0.07       0
  5154.2   0.035       0  5190.5    0.07       0
Bank Sta=4969.5,5006.5
Exp/Cntr=0.3,0.1

Type RM Length L Ch R = 1,14617,486,486,486
BEGIN DESCRIPTION:
Mapping XS 481e7592
END DESCRIPTION:
XS GIS Cut Line= 3
      1664923.47      7006819.73      1664046.76      7007349.23
      1663230.79      7008078.39
#Sta/Elev= 30
  3983.2 1571.72  4068.0 1564.46  4242.6 1532.75  4414.3 1525.02  4422.4 1524.62
  4542.4 1520.80  4767.3 1515.13  4978.1 1510.41  4986.1 1506.01  4986.7 1498.18
  4987.7 1497.68  5024.3 1498.18  5036.5 1502.47  5057.4 1505.20  5142.7 1504.55
  5277.2 1507.54  5291.4 1508.83  5298.2 1511.78  5304.9 1510.82  5312.4 1513.94
  5319.1 1512.64  5326.6 1516.00  5333.3 1514.41  5355.0 1519.35  5418.5 1525.54
  5432.7 1529.83  5475.4 1534.24  5659.3 1543.39  5942.7 1567.42  6101.7 1575.28
#Mann=7,-1,0
  3983.2    0.07       0  4414.3   0.035       0  4422.4    0.07       0
  4542.4   0.035       0  4767.3    0.07       0  4986.7    0.07       0
  5024.3    0.07       0
Bank Sta=4986.7,5024.3
Exp/Cntr=0.3,0.1

Type RM Length L Ch R = 1,14131,495,495,495
BEGIN DESCRIPTION:
Mapping XS a31fc025
END DESCRIPTION:
XS GIS Cut Line= 3
      1664489.45      7006403.07      1663734.26      7006988.99
      1662996.64      7008043.35
#Sta/Elev= 30
  4060.0 1544.82  4173.6 1542.56  4294.0 1529.62  4352.6 1526.66  4378.5 1525.93
  4522.1 1521.91  4686.0 1513.40  4893.3 1512.57  4922.2 1508.41  4928.6 1503.12
  4972.0 1502.93  4978.3 1499.75  5001.0 1497.14  5009.2 1493.07  5010.2 1492.57
  5046.9 1493.07  5051.2 1497.21  5063.8 1503.15  5078.7 1506.44  5158.5 1507.85
  5342.3 1512.03  5417.4 1515.46  5459.7 1520.90  5510.3 1531.12  5558.6 1534.87
  5594.3 1536.48  5703.9 1543.23  5826.0 1557.53  6022.3 1569.48  6302.6 1578.48
#Mann=10,-1,0
  4060.0    0.07       0  4352.6   0.035       0  4378.5    0.07       0
  5009.2    0.07       0  5046.9    0.07       0  5158.5   0.035       0
  5342.3    0.07       0  5558.6   0.035       0  5594.3    0.07       0
  6022.3   0.035       0
Bank Sta=5009.2,5046.9
Exp/Cntr=0.3,0.1

Type RM Length L Ch R = 1,13636,281,281,281
BEGIN DESCRIPTION:
Mapping XS d15ac262
END DESCRIPTION:
XS GIS Cut Line= 3
      1663834.07      7006550.63      1663321.93      7006763.30
      1662727.32      7008039.32
#Sta/Elev= 30
  4451.9 1521.57  4538.0 1520.68  4644.8 1519.93  4850.9 1518.13  4900.8 1516.05
  4916.5 1512.97  4930.1 1507.25  4966.6 1497.58  4977.8 1496.69  4983.2 1493.51
  4995.2 1490.88  4996.2 1490.38  5032.9 1490.88  5054.3 1497.34  5088.9 1502.30
  5159.3 1506.18  5170.3 1506.62  5232.3 1508.58  5265.4 1507.19  5294.0 1509.61
  5413.9 1512.64  5465.2 1519.41  5505.4 1527.05  5533.8 1535.09  5596.3 1541.92
  5676.5 1555.82  5806.0 1566.22  5912.5 1568.40  6361.8 1575.44  6414.2 1574.64
#Mann=10,-1,0
  4451.9    0.07       0  4538.0   0.035       0  4644.8    0.07       0
  4850.9    0.16       0  4966.6    0.07       0  4995.2    0.07       0
  5032.9    0.07       0  5159.3   0.035       0  5170.3    0.07       0
  5912.5   0.035       0
Bank Sta=4995.2,5032.9
Exp/Cntr=0.3,0.1

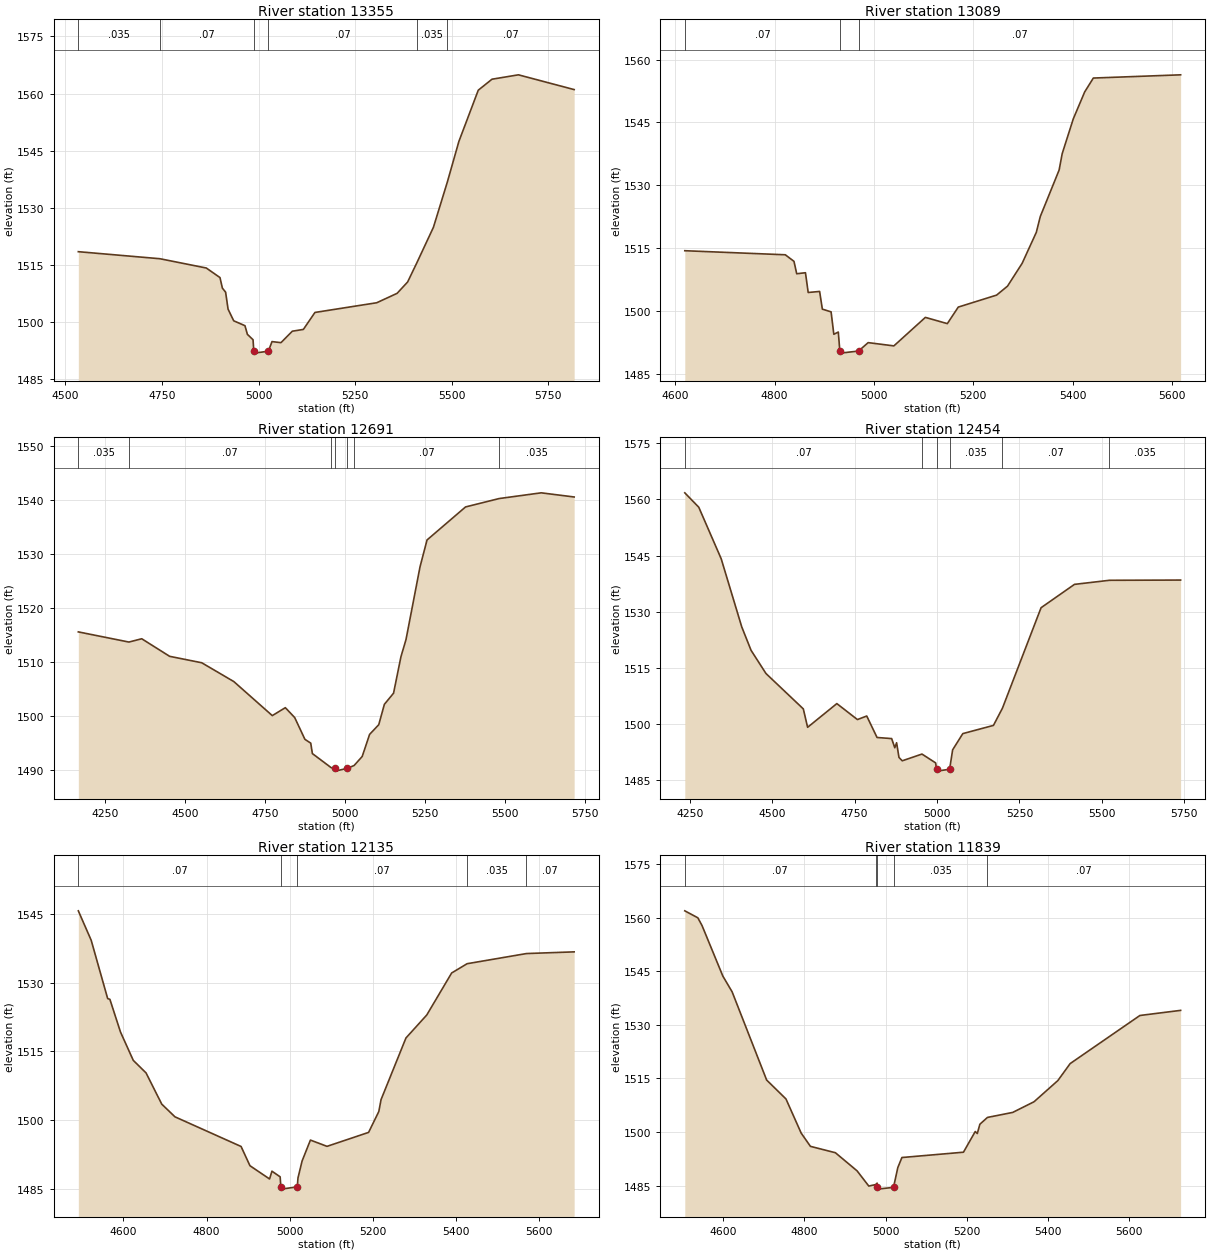
Type RM Length L Ch R = 1,13355,266,266,266
BEGIN DESCRIPTION:
Mapping XS 0f837413
END DESCRIPTION:
XS GIS Cut Line= 3
      1663453.74      7006384.09      1663068.28      7006668.84
      1662659.39      7007361.88
#Sta/Elev= 30
  4533.4 1518.43  4744.5 1516.58  4864.7 1514.14  4900.2 1511.63  4906.4 1508.86
  4914.8 1507.79  4921.1 1503.34  4935.7 1500.27  4964.9 1498.98  4971.2 1496.70
  4985.8 1495.29  4987.8 1492.27  4988.7 1491.77  5025.5 1492.27  5034.9 1494.80
  5058.1 1494.52  5087.5 1497.53  5116.1 1498.00  5146.1 1502.46  5306.1 1505.01
  5358.8 1507.48  5386.1 1510.47  5410.4 1515.60  5452.9 1524.84  5489.0 1536.76
  5518.8 1547.40  5569.0 1560.87  5604.6 1563.76  5673.0 1564.91  5817.3 1561.03
#Mann=6,-1,0
  4533.4   0.035       0  4744.5    0.07       0  4987.8    0.07       0
  5025.5    0.07       0  5410.4   0.035       0  5489.0    0.07       0
Bank Sta=4987.8,5025.5
Exp/Cntr=0.3,0.1

Type RM Length L Ch R = 1,13089,398,398,398
BEGIN DESCRIPTION:
Mapping XS ed915a54
END DESCRIPTION:
XS GIS Cut Line= 3
      1663166.17      7006480.04      1662811.99      7006641.50
      1662557.50      7007194.62
#Sta/Elev= 30
  4619.2 1514.36  4821.5 1513.39  4839.0 1511.82  4844.5 1508.86  4862.1 1509.10
  4867.6 1504.38  4890.6 1504.63  4896.1 1500.40  4913.7 1499.75  4919.2 1494.39
  4928.2 1494.93  4931.3 1490.39  4932.3 1489.89  4969.0 1490.39  4988.3 1492.40
  5040.1 1491.62  5103.5 1498.43  5147.7 1496.94  5169.7 1500.89  5246.8 1503.75
  5268.8 1505.89  5298.3 1511.35  5326.8 1518.75  5334.8 1522.53  5372.7 1533.63
  5378.9 1537.55  5401.2 1545.86  5424.2 1552.31  5441.6 1555.62  5617.3 1556.39
#Mann=3,-1,0
  4619.2    0.07       0  4931.3    0.07       0  4969.0    0.07       0
Bank Sta=4931.3,4969
Exp/Cntr=0.3,0.1

Type RM Length L Ch R = 1,12691,237,237,237
BEGIN DESCRIPTION:
Fish Creek 25.0
END DESCRIPTION:
XS GIS Cut Line= 3
      1663259.29      7006404.95      1662441.83      7006574.26
      1662148.13      7007227.91
#Sta/Elev= 30
  4165.2 1515.64  4323.5 1513.76  4363.6 1514.37  4450.9 1511.12  4551.3 1509.93
  4651.7 1506.45  4772.1 1500.15  4812.9 1501.62  4842.2 1499.79  4874.2 1495.76
  4892.4 1495.06  4897.5 1493.13  4956.3 1490.52  4967.7 1490.38  4968.7 1489.88
  5005.4 1490.38  5027.9 1490.91  5053.4 1492.59  5076.5 1496.67  5105.2 1498.47
  5122.8 1502.24  5151.5 1504.30  5174.6 1511.04  5190.5 1514.23  5234.3 1527.67
  5256.3 1532.65  5376.8 1538.76  5481.8 1540.31  5613.5 1541.37  5716.6 1540.60
#Mann=7,-1,0
  4165.2   0.035       0  4323.5    0.07       0  4956.3   0.035       0
  4967.7   0.035       0  5005.4   0.035       0  5027.9    0.07       0
  5481.8   0.035       0
Bank Sta=4967.7,5005.4
Exp/Cntr=0.3,0.1

Type RM Length L Ch R = 1,12454,319,319,319
BEGIN DESCRIPTION:
Mapping XS e6801966
END DESCRIPTION:
XS GIS Cut Line= 3
      1661922.99      7005752.03      1662253.73      7006442.14
      1662071.43      7007158.33
#Sta/Elev= 30
  4234.9 1561.78  4277.3 1557.93  4345.3 1544.16  4407.7 1525.94  4435.9 1519.69
  4481.2 1513.48  4594.5 1504.02  4607.5 1499.10  4696.2 1505.44  4758.7 1501.17
  4786.9 1502.12  4818.2 1496.38  4862.5 1496.09  4872.0 1493.64  4877.5 1494.98
  4884.7 1491.05  4894.6 1490.15  4954.5 1491.95  4995.9 1489.59  4998.7 1487.89
  4999.7 1487.39  5038.3 1487.89  5047.5 1493.08  5078.4 1497.42  5171.3 1499.61
  5198.6 1504.21  5315.8 1531.07  5417.2 1537.31  5523.2 1538.40  5739.2 1538.46
#Mann=6,-1,0
  4234.9    0.07       0  4954.5   0.035       0  4998.7   0.035       0
  5038.3   0.035       0  5198.6    0.07       0  5523.2   0.035       0
Bank Sta=4998.7,5038.3
Exp/Cntr=0.3,0.1

Type RM Length L Ch R = 1,12135,296,296,296
BEGIN DESCRIPTION:
Mapping XS b94b7e8a
END DESCRIPTION:
XS GIS Cut Line= 3
      1661795.38      7005858.78      1661967.27      7006340.58
      1661943.83      7007022.83
#Sta/Elev= 30
  4491.3 1545.70  4522.3 1539.26  4562.0 1526.51  4567.3 1526.36  4592.8 1519.22
  4623.6 1513.02  4654.4 1510.27  4692.2 1503.45  4724.1 1500.67  4883.3 1494.19
  4904.6 1489.99  4951.9 1487.09  4957.6 1488.79  4977.4 1487.56  4979.0 1485.37
  4980.0 1484.87  5018.7 1485.37  5020.3 1487.30  5030.3 1491.04  5050.3 1495.59
  5090.3 1494.22  5190.4 1497.27  5215.0 1501.83  5220.4 1504.43  5280.4 1517.91
  5330.5 1522.93  5390.5 1532.12  5427.7 1534.14  5570.6 1536.36  5685.5 1536.73
#Mann=5,-1,0
  4491.3    0.07       0  4979.0    0.07       0  5018.7    0.07       0
  5427.7   0.035       0  5570.6    0.07       0
Bank Sta=4979,5018.7
Exp/Cntr=0.3,0.1

Type RM Length L Ch R = 1,11839,375,375,375
BEGIN DESCRIPTION:
Mapping XS 38b847c0
END DESCRIPTION:
XS GIS Cut Line= 3
      1661574.05      7005806.76      1661688.62      7006296.31
      1661792.79      7007007.24
#Sta/Elev= 30
  4505.4 1561.88  4537.5 1559.93  4547.8 1557.78  4599.1 1543.63  4622.0 1539.21
  4707.0 1514.54  4754.6 1509.25  4792.0 1499.71  4814.8 1495.99  4876.4 1494.20
  4929.7 1489.14  4958.6 1484.88  4975.5 1485.29  4979.1 1485.69  4979.8 1484.52
  4980.8 1484.02  5019.5 1484.52  5030.1 1490.05  5040.2 1492.86  5191.8 1494.35
  5220.8 1500.14  5225.9 1499.58  5232.2 1502.17  5250.9 1504.08  5313.1 1505.48
  5365.6 1508.46  5424.3 1514.39  5454.6 1519.14  5626.4 1532.60  5726.7 1534.03
#Mann=5,-1,0
  4505.4    0.07       0  4975.5   0.035       0  4979.8   0.035       0
  5019.5   0.035       0  5250.9    0.07       0
Bank Sta=4979.8,5019.5
Exp/Cntr=0.3,0.1

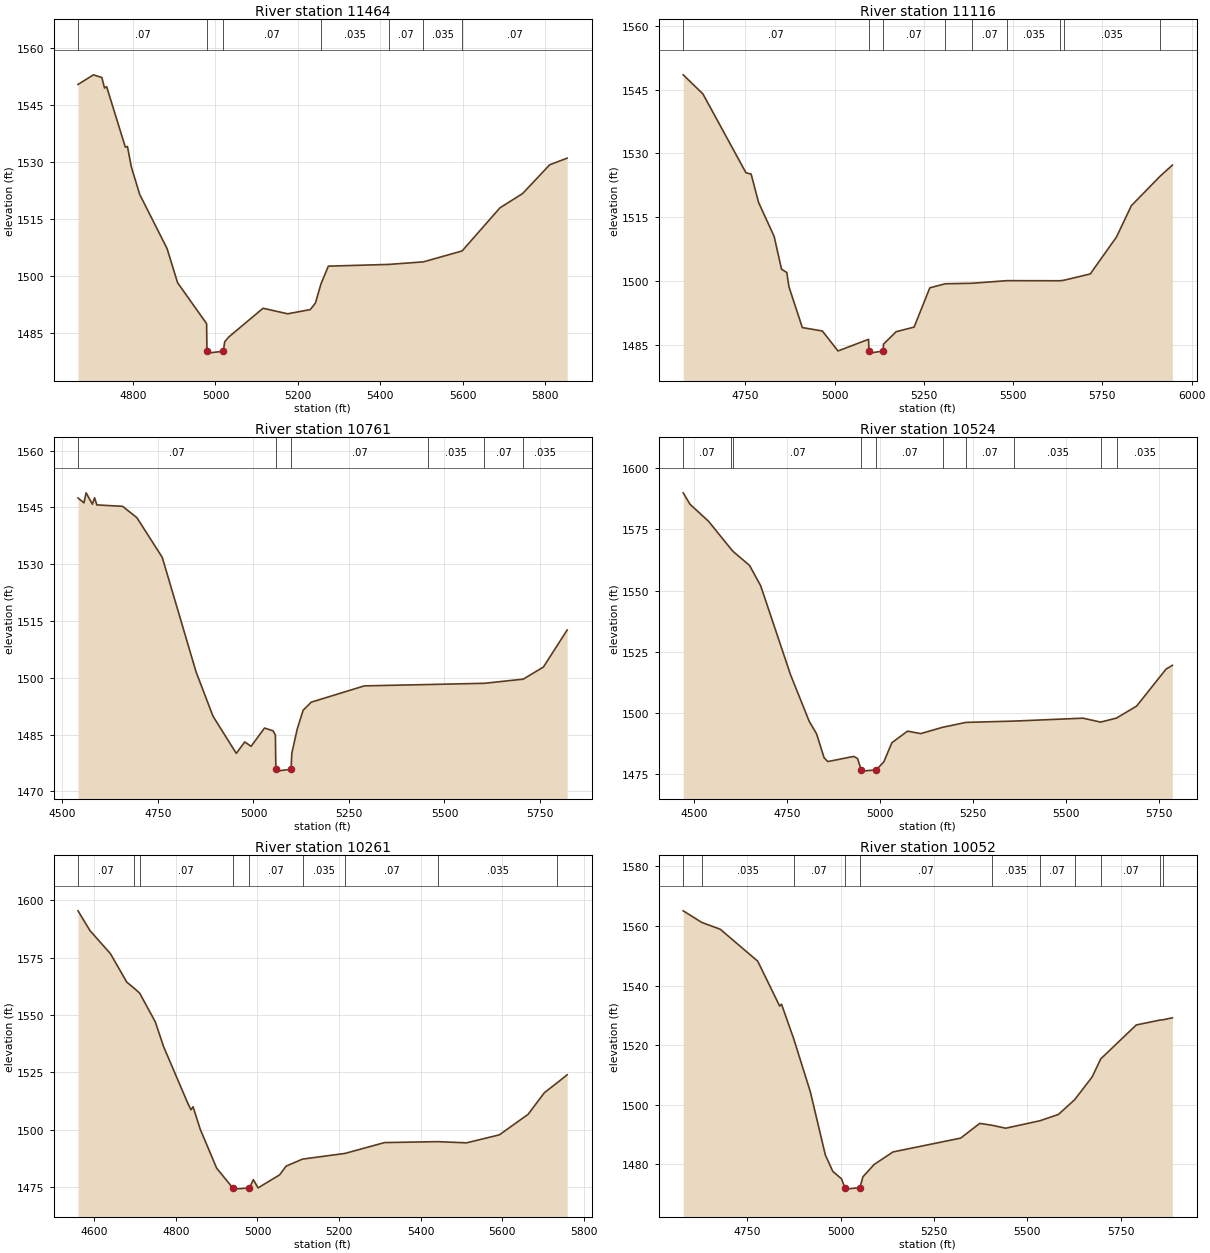
Type RM Length L Ch R = 1,11464,348,348,348
BEGIN DESCRIPTION:
Mapping XS 8cc81690
END DESCRIPTION:
XS GIS Cut Line= 3
      1661276.88      7005861.39      1661344.15      7006191.24
      1661690.68      7006966.59
#Sta/Elev= 30
  4666.8 1550.49  4704.2 1553.03  4724.6 1552.33  4731.1 1549.55  4736.2 1549.93
  4781.6 1534.00  4786.7 1534.17  4796.0 1528.85  4816.4 1521.56  4882.7 1507.32
  4908.3 1498.31  4978.6 1487.54  4979.4 1480.29  4980.4 1479.79  5019.1 1480.29
  5022.5 1482.80  5032.7 1484.07  5115.4 1491.60  5175.1 1490.14  5229.9 1491.25
  5242.3 1492.95  5255.6 1497.92  5273.7 1502.68  5420.8 1503.14  5504.3 1503.81
  5598.0 1506.68  5689.9 1518.04  5744.7 1521.78  5810.4 1529.36  5852.7 1531.10
#Mann=7,-1,0
  4666.8    0.07       0  4979.4    0.07       0  5019.1    0.07       0
  5255.6   0.035       0  5420.8    0.07       0  5504.3   0.035       0
  5598.0    0.07       0
Bank Sta=4979.4,5019.1
Exp/Cntr=0.3,0.1

Type RM Length L Ch R = 1,11116,355,355,355
BEGIN DESCRIPTION:
Mapping XS fb61af78
END DESCRIPTION:
XS GIS Cut Line= 3
      1660753.89      7005902.63      1661012.12      7006241.15
      1661569.08      7007004.00
#Sta/Elev= 30
  4575.7 1548.45  4630.9 1543.96  4751.5 1525.44  4766.0 1525.11  4786.8 1518.46
  4830.4 1510.48  4851.2 1502.75  4865.8 1502.00  4872.0 1498.61  4909.4 1489.05
  4965.5 1488.24  5009.3 1483.55  5095.0 1486.29  5095.9 1483.54  5096.9 1483.04
  5135.8 1483.54  5136.8 1485.15  5172.3 1488.08  5222.5 1489.16  5266.5 1498.39
  5309.5 1499.34  5384.6 1499.46  5482.4 1500.07  5632.4 1500.05  5643.2 1500.19
  5716.0 1501.65  5789.4 1510.33  5831.1 1517.70  5911.9 1524.64  5946.0 1527.23
#Mann=9,-1,0
  4575.7    0.07       0  5095.9    0.07       0  5135.8    0.07       0
  5309.5   0.035       0  5384.6    0.07       0  5482.4   0.035       0
  5632.4    0.07       0  5643.2   0.035       0  5911.9    0.07       0
Bank Sta=5095.9,5135.8
Exp/Cntr=0.3,0.1

Type RM Length L Ch R = 1,10761,237,237,237
BEGIN DESCRIPTION:
Mapping XS b341b6e1
END DESCRIPTION:
XS GIS Cut Line= 3
      1660560.30      7006064.08      1660771.23      7006472.92
      1661460.71      7006917.83
#Sta/Elev= 30
  4540.6 1547.52  4556.2 1546.22  4561.8 1548.87  4578.3 1545.87  4584.0 1547.58
  4590.0 1545.68  4657.5 1545.30  4694.8 1542.31  4761.2 1531.82  4849.9 1501.51
  4894.2 1489.84  4955.0 1480.05  4977.2 1483.07  4993.7 1481.91  5028.9 1486.74
  5051.4 1486.01  5057.4 1484.87  5058.6 1475.86  5059.6 1475.36  5098.5 1475.86
  5100.3 1480.05  5114.8 1486.58  5130.0 1491.45  5151.1 1493.57  5290.3 1497.88
  5456.3 1498.23  5604.6 1498.56  5706.1 1499.65  5758.9 1502.84  5821.2 1512.63
#Mann=6,-1,0
  4540.6    0.07       0  5058.6    0.07       0  5098.5    0.07       0
  5456.3   0.035       0  5604.6    0.07       0  5706.1   0.035       0
Bank Sta=5058.6,5098.5
Exp/Cntr=0.3,0.1

Type RM Length L Ch R = 1,10524,263,263,263
BEGIN DESCRIPTION:
Mapping XS 68e95a91
END DESCRIPTION:
XS GIS Cut Line= 3
      1660226.95      7006717.72      1660755.61      7006704.70
      1661487.37      7006988.55
#Sta/Elev= 30
  4471.8 1589.86  4489.9 1585.22  4539.9 1578.25  4601.2 1566.75  4606.8 1565.82
  4649.9 1560.26  4679.9 1551.95  4759.9 1515.74  4809.9 1496.77  4830.0 1491.56
  4850.0 1481.89  4860.0 1480.27  4930.0 1482.37  4940.0 1481.53  4949.7 1476.87
  4950.7 1476.37  4990.3 1476.87  5010.7 1480.18  5032.1 1487.95  5074.3 1492.68
  5109.6 1491.67  5169.1 1494.27  5231.0 1496.24  5361.2 1496.78  5545.3 1497.96
  5592.6 1496.37  5635.6 1498.01  5689.5 1502.90  5768.5 1517.97  5785.5 1519.51
#Mann=10,-1,0
  4471.8    0.07       0  4601.2   0.035       0  4606.8    0.07       0
  4949.7    0.07       0  4990.3    0.07       0  5169.1   0.035       0
  5231.0    0.07       0  5361.2   0.035       0  5592.6    0.07       0
  5635.6   0.035       0
Bank Sta=4949.7,4990.3
Exp/Cntr=0.3,0.1

Type RM Length L Ch R = 1,10261,209,209,209
BEGIN DESCRIPTION:
Mapping XS a1c29fe4
END DESCRIPTION:
XS GIS Cut Line= 3
      1660315.49      7006954.69      1660753.01      7006967.72
      1661510.39      7007040.59
#Sta/Elev= 30
  4560.3 1595.49  4589.8 1586.83  4639.8 1576.79  4679.9 1564.36  4697.6 1561.77
  4711.6 1559.51  4749.9 1546.96  4769.9 1536.28  4829.9 1511.27  4837.2 1508.64
  4842.2 1509.98  4859.9 1500.13  4900.0 1483.18  4939.7 1474.52  4940.7 1474.02
  4980.3 1474.52  4990.0 1478.13  5001.5 1474.56  5054.2 1480.23  5070.3 1484.06
  5110.4 1487.12  5214.6 1489.61  5311.4 1494.34  5442.7 1494.74  5512.4 1494.22
  5592.7 1497.71  5663.1 1506.65  5703.2 1516.13  5734.8 1520.50  5758.9 1523.92
#Mann=9,-1,0
  4560.3    0.07       0  4697.6   0.035       0  4711.6    0.07       0
  4939.7    0.07       0  4980.3    0.07       0  5110.4   0.035       0
  5214.6    0.07       0  5442.7   0.035       0  5734.8    0.07       0
Bank Sta=4939.7,4980.3
Exp/Cntr=0.3,0.1

Type RM Length L Ch R = 1,10052,503,503,503
BEGIN DESCRIPTION:
Mapping XS c6ddb96f
END DESCRIPTION:
XS GIS Cut Line= 3
      1660336.34      7007220.32      1660758.21      7007176.05
      1661638.38      7007071.89
#Sta/Elev= 30
  4578.0 1565.11  4627.8 1561.21  4677.2 1558.93  4777.7 1548.20  4836.4 1533.14
  4841.4 1533.77  4873.7 1522.29  4918.5 1504.41  4958.7 1483.20  4978.8 1477.65
  5002.2 1475.15  5010.9 1472.20  5011.9 1471.70  5051.5 1472.20  5059.4 1475.84
  5089.6 1479.98  5139.9 1484.18  5321.2 1488.82  5372.5 1493.76  5405.1 1493.14
  5442.0 1492.15  5533.6 1494.65  5583.0 1496.75  5626.6 1501.70  5673.6 1509.36
  5696.6 1515.41  5791.7 1526.80  5855.7 1528.45  5862.6 1528.52  5888.5 1529.20
#Mann=11,-1,0
  4578.0    0.07       0  4627.8   0.035       0  4873.7    0.07       0
  5010.9    0.07       0  5051.5    0.07       0  5405.1   0.035       0
  5533.6    0.07       0  5626.6   0.035       0  5696.6    0.07       0
  5855.7   0.035       0  5862.6    0.07       0
Bank Sta=5010.9,5051.5
Exp/Cntr=0.3,0.1

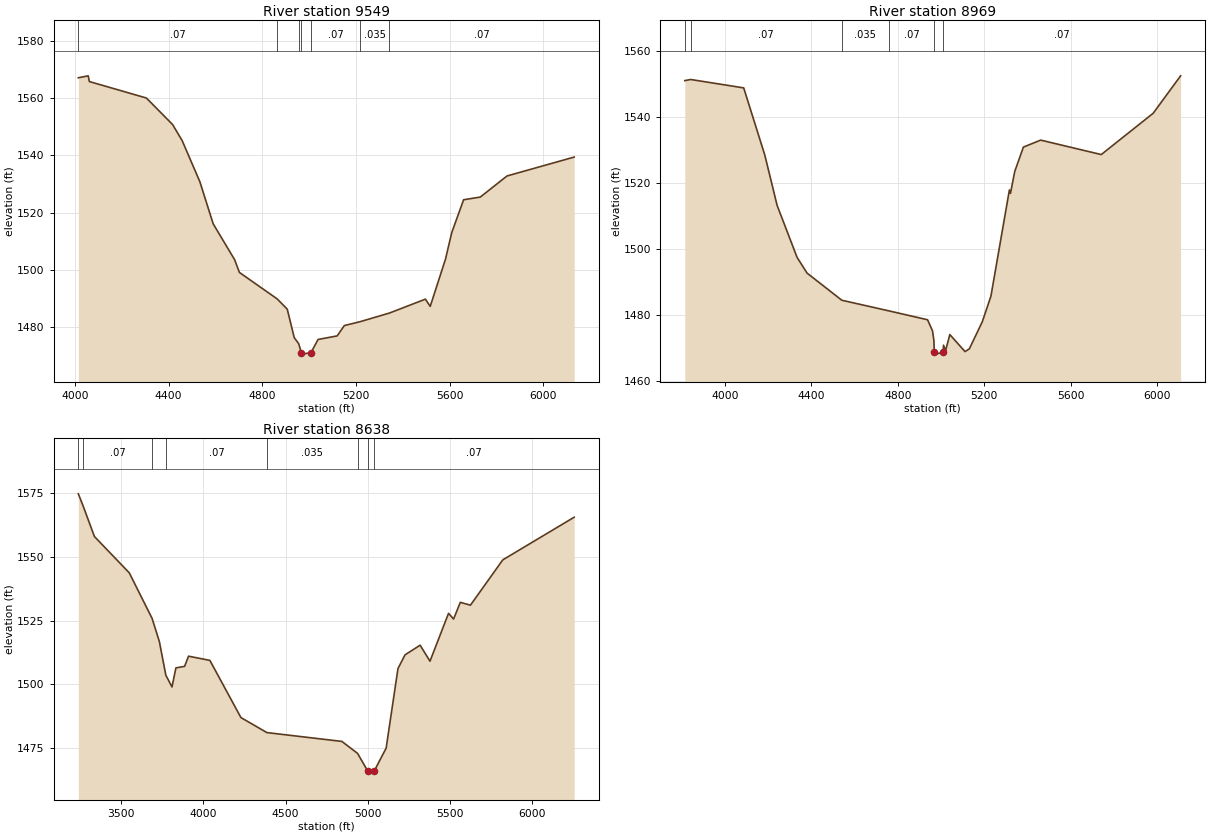
Type RM Length L Ch R = 1,9549,580,580,580
BEGIN DESCRIPTION:
Mapping XS 6c09707a
END DESCRIPTION:
XS GIS Cut Line= 3
      1659939.47      7007444.89      1660907.35      7007631.52
      1662018.44      7007848.53
#Sta/Elev= 30
  4014.4 1567.24  4056.5 1567.92  4061.6 1565.91  4305.2 1560.14  4417.2 1550.83
  4458.0 1545.19  4533.5 1530.81  4590.4 1516.04  4682.0 1503.47  4702.4 1499.01
  4863.4 1489.75  4906.7 1486.14  4936.6 1476.15  4955.5 1474.03  4967.2 1470.87
  4968.2 1470.37  5007.8 1470.87  5038.5 1475.51  5120.0 1476.76  5150.6 1480.38
  5219.3 1481.77  5342.9 1484.76  5497.0 1489.64  5517.4 1487.10  5582.6 1503.66
  5609.1 1512.90  5660.0 1524.48  5731.3 1525.42  5845.5 1532.82  6132.2 1539.44
#Mann=7,-1,0
  4014.4    0.07       0  4863.4   0.035       0  4955.5    0.07       0
  4967.2    0.07       0  5007.8    0.07       0  5219.3   0.035       0
  5342.9    0.07       0
Bank Sta=4967.2,5007.8
Exp/Cntr=0.3,0.1

Type RM Length L Ch R = 1,8969,331,331,331
BEGIN DESCRIPTION:
Mapping XS ee8815a9
END DESCRIPTION:
XS GIS Cut Line= 3
      1659926.47      7007687.95      1661011.51      7008182.73
      1662111.93      7008148.07
#Sta/Elev= 30
  3814.5 1550.98  3841.8 1551.32  4087.0 1548.78  4184.6 1528.45  4241.7 1513.20
  4333.9 1497.50  4380.0 1492.75  4541.0 1484.53  4757.8 1481.33  4937.4 1478.63
  4960.4 1475.25  4966.9 1472.28  4968.6 1468.73  4969.6 1468.23  5009.3 1468.73
  5011.3 1470.93  5020.5 1469.23  5040.5 1474.15  5110.6 1469.00  5130.6 1469.82
  5190.6 1478.02  5230.6 1485.78  5316.0 1517.90  5321.0 1516.88  5340.7 1523.49
  5380.7 1530.86  5460.7 1532.98  5740.9 1528.61  5981.0 1541.10  6108.0 1552.43
#Mann=6,-1,0
  3814.5   0.035       0  3841.8    0.07       0  4541.0   0.035       0
  4757.8    0.07       0  4968.6    0.07       0  5009.3    0.07       0
Bank Sta=4968.6,5009.3
Exp/Cntr=0.3,0.1

Type RM Length L Ch R = 1,8638,362,362,362
BEGIN DESCRIPTION:
Mapping XS 21086214
END DESCRIPTION:
XS GIS Cut Line= 3
      1659323.16      7007813.82      1660950.75      7008495.23
      1662170.20      7008768.63
#Sta/Elev= 30
  3239.5 1574.55  3269.2 1569.72  3337.3 1557.86  3549.3 1543.65  3688.0 1525.82
  3732.1 1516.79  3771.6 1503.61  3808.9 1499.05  3832.6 1506.49  3885.6 1507.09
  3909.4 1511.07  4039.2 1509.42  4228.0 1487.06  4386.0 1481.19  4841.7 1477.74
  4937.1 1473.06  4998.2 1466.23  4999.2 1465.73  5038.9 1466.23  5110.8 1475.11
  5182.6 1506.22  5225.5 1511.58  5317.3 1515.36  5377.3 1509.11  5490.0 1527.82
  5520.7 1525.60  5561.7 1532.12  5623.2 1531.01  5819.8 1548.72  6253.7 1565.40
#Mann=8,-1,0
  3239.5   0.035       0  3269.2    0.07       0  3688.0   0.035       0
  3771.6    0.07       0  4386.0   0.035       0  4937.1    0.07       0
  4998.2    0.07       0  5038.9    0.07       0
Bank Sta=4998.2,5038.9
Exp/Cntr=0.3,0.1