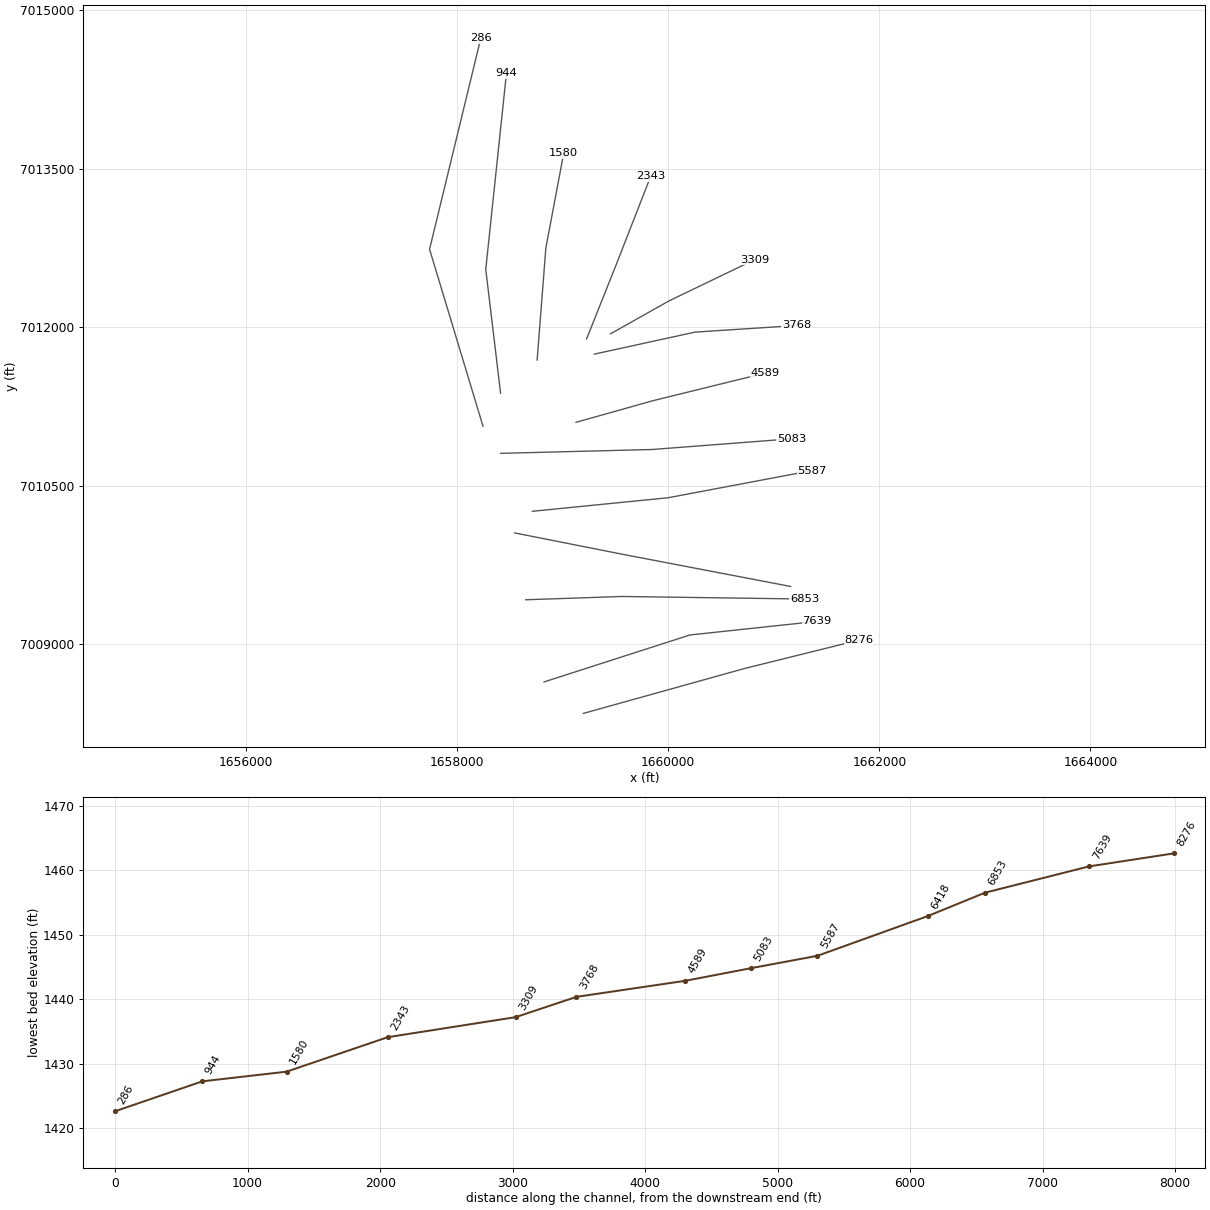
HEC-RAS study Fish Creek.prj: Fish Creek Base Level Engineering

--- Fish Creek.g01 (geometry) --- (continued)

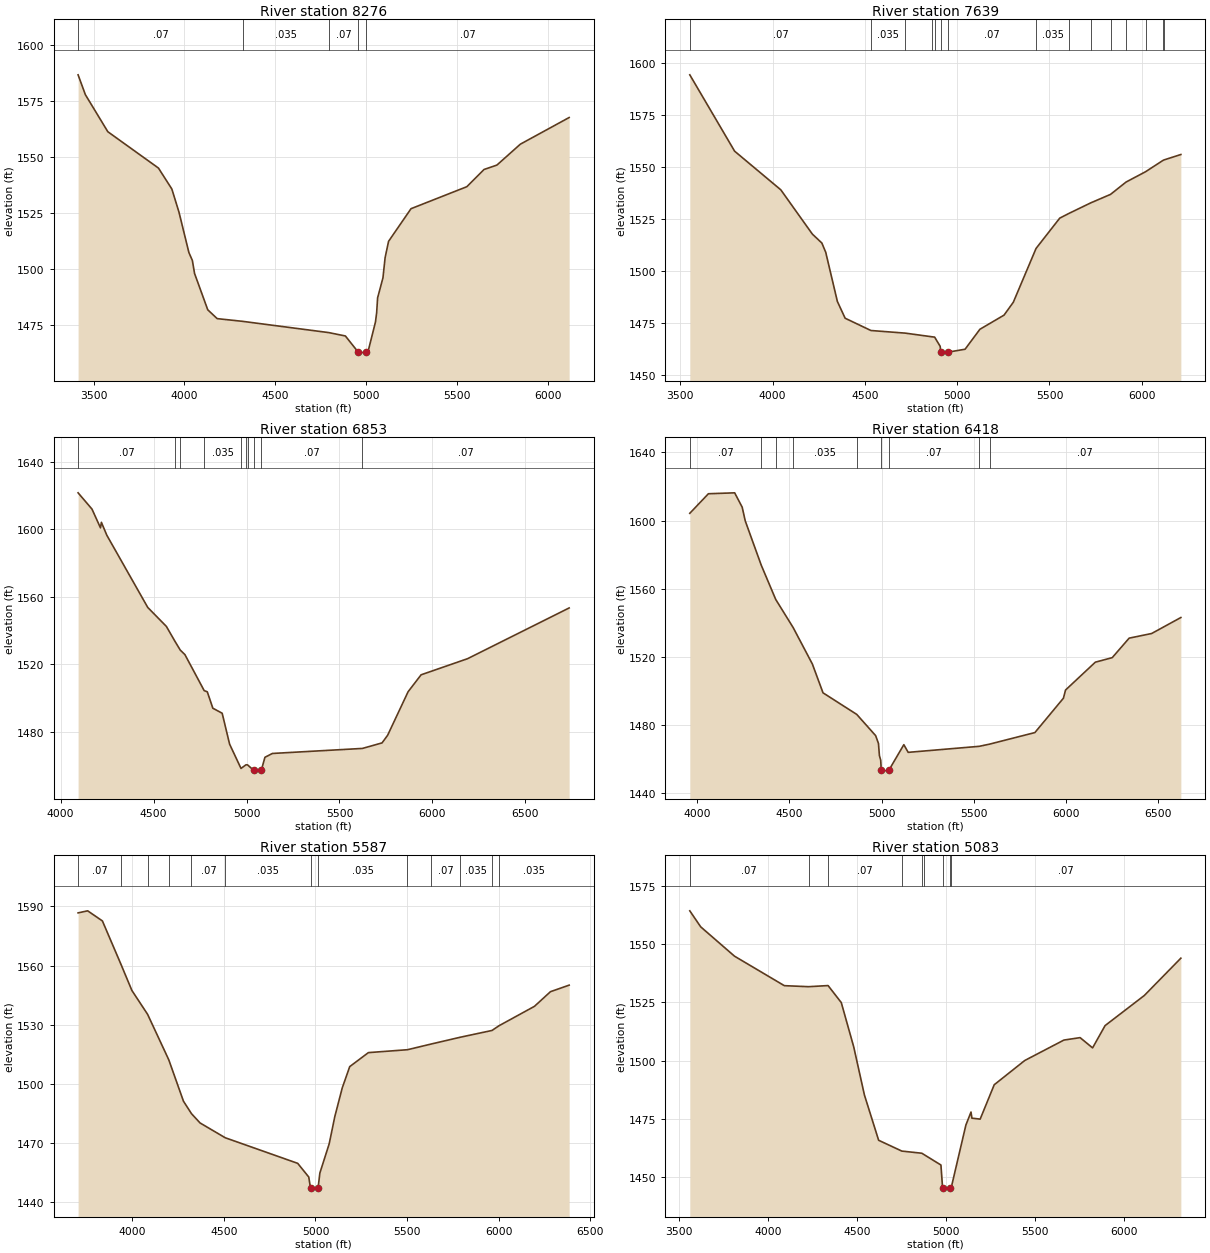
Type RM Length L Ch R = 1,8276,637,637,637
BEGIN DESCRIPTION:
Mapping XS 8ad5a4dd
END DESCRIPTION:
XS GIS Cut Line= 3
      1659197.24      7008343.31      1660725.05      7008768.67
      1661810.07      7009037.75
#Sta/Elev= 30
  3414.5 1586.55  3454.7 1577.69  3578.3 1561.21  3857.0 1545.03  3930.7 1535.71
  3970.1 1525.37  4024.6 1507.41  4043.7 1503.91  4055.8 1498.09  4128.4 1481.93
  4180.3 1477.99  4320.5 1476.78  4794.7 1471.77  4886.2 1470.27  4956.4 1463.13
  4957.4 1462.63  4997.2 1463.13  5010.7 1463.23  5051.9 1476.49  5058.5 1480.73
  5063.6 1487.22  5093.1 1496.17  5105.0 1505.16  5124.0 1512.41  5247.6 1526.94
  5555.0 1536.74  5649.4 1544.39  5720.5 1546.36  5849.8 1555.68  6118.3 1567.54
#Mann=5,-1,0
  3414.5    0.07       0  4320.5   0.035       0  4794.7    0.07       0
  4956.4    0.07       0  4997.2    0.07       0
Bank Sta=4956.4,4997.2
Exp/Cntr=0.3,0.1

Type RM Length L Ch R = 1,7639,786,786,786
BEGIN DESCRIPTION:
Mapping XS d5555a37
END DESCRIPTION:
XS GIS Cut Line= 3
      1658823.98      7008641.06      1660205.96      7009085.51
      1661407.32      7009213.98
#Sta/Elev= 30
  3551.8 1594.49  3794.5 1557.77  4044.7 1539.18  4215.6 1517.89  4267.2 1513.57
  4288.2 1509.09  4351.2 1485.47  4393.2 1477.41  4532.9 1471.50  4718.8 1470.24
  4862.7 1468.49  4877.9 1468.33  4907.9 1463.90  4911.6 1461.12  4912.6 1460.62
  4952.5 1461.12  5042.8 1462.49  5123.2 1472.09  5253.9 1478.90  5304.2 1485.10
  5427.4 1510.99  5555.7 1525.56  5605.7 1527.83  5722.6 1532.86  5830.8 1536.98
  5915.0 1542.92  6020.5 1547.88  6113.2 1553.22  6119.9 1553.54  6211.7 1556.16
#Mann=15,-1,0
  3551.8    0.07       0  4532.9   0.035       0  4718.8    0.07       0
  4862.7   0.035       0  4877.9    0.07       0  4911.6    0.07       0
  4952.5    0.07       0  5427.4   0.035       0  5605.7    0.07       0
  5722.6   0.035       0  5830.8    0.07       0  5915.0   0.035       0
  6020.5    0.07       0  6113.2   0.035       0  6119.9    0.07       0
Bank Sta=4911.6,4952.5
Exp/Cntr=0.3,0.1

Type RM Length L Ch R = 1,6853,435,435,435
BEGIN DESCRIPTION:
Mapping XS ae0f531c
END DESCRIPTION:
XS GIS Cut Line= 3
      1658650.39      7009418.84      1659560.12      7009450.09
      1661291.39      7009425.81
#Sta/Elev= 30
  4093.9 1621.55  4168.6 1611.91  4214.3 1600.80  4219.3 1604.06  4248.6 1596.38
  4468.7 1553.59  4568.8 1542.35  4614.1 1533.69  4643.5 1528.32  4668.8 1525.59
  4772.2 1504.28  4788.9 1503.57  4818.9 1493.83  4869.0 1490.87  4909.0 1472.53
  4970.3 1458.14  4997.4 1460.31  5005.4 1460.24  5038.6 1457.04  5039.6 1456.54
  5079.5 1457.04  5099.1 1464.74  5139.1 1467.01  5623.7 1470.00  5729.1 1473.28
  5759.1 1477.79  5869.1 1503.59  5939.1 1513.65  6189.2 1523.21  6735.6 1553.29
#Mann=10,-1,0
  4093.9    0.07       0  4614.1   0.035       0  4643.5    0.07       0
  4772.2   0.035       0  4970.3    0.07       0  4997.4   0.035       0
  5005.4    0.07       0  5038.6   0.035       0  5079.5    0.07       0
  5623.7    0.07       0
Bank Sta=5038.6,5079.5
Exp/Cntr=0.3,0.1

Type RM Length L Ch R = 1,6418,831,831,831
BEGIN DESCRIPTION:
Mapping XS 7fd1b318
END DESCRIPTION:
XS GIS Cut Line= 3
      1658546.34      7010051.66      1659563.73      7009850.27
      1661160.44      7009544.81
#Sta/Elev= 30
  3959.5 1604.25  4060.4 1615.72  4202.8 1616.26  4243.6 1607.82  4260.2 1599.78
  4346.8 1573.82  4425.5 1553.66  4519.9 1537.18  4624.0 1515.80  4681.9 1498.85
  4864.9 1486.18  4967.3 1473.72  4982.6 1469.11  4987.7 1461.97  4994.7 1459.32
  4997.8 1453.39  4998.8 1452.89  5038.8 1453.39  5120.1 1468.41  5143.7 1463.91
  5528.8 1467.45  5584.8 1468.73  5830.7 1475.52  5985.5 1495.70  5997.0 1500.50
  6158.6 1516.85  6250.2 1519.51  6341.9 1530.95  6464.0 1533.68  6622.3 1543.06
#Mann=9,-1,0
  3959.5    0.07       0  4346.8   0.035       0  4425.5    0.07       0
  4519.9   0.035       0  4864.9    0.07       0  4997.8    0.07       0
  5038.8    0.07       0  5528.8   0.035       0  5584.8    0.07       0
Bank Sta=4997.8,5038.8
Exp/Cntr=0.3,0.1

Type RM Length L Ch R = 1,5587,504,504,504
BEGIN DESCRIPTION:
Mapping XS 1459f8b4
END DESCRIPTION:
XS GIS Cut Line= 3
      1658713.04      7010256.52      1660001.23      7010384.99
      1661361.13      7010641.71
#Sta/Elev= 30
  3705.4 1586.70  3757.6 1587.74  3838.0 1582.62  3937.5 1561.03  3998.8 1547.40
  4084.7 1535.28  4200.1 1512.25  4280.2 1491.28  4323.8 1484.99  4370.5 1480.28
  4507.9 1472.77  4903.3 1459.80  4963.6 1452.87  4973.1 1447.24  4974.1 1446.74
  5014.3 1447.24  5024.2 1454.90  5075.1 1469.72  5105.6 1483.46  5146.1 1497.98
  5187.0 1508.81  5288.8 1515.90  5501.9 1517.37  5629.4 1520.21  5789.8 1523.69
  5963.2 1527.13  6000.0 1529.45  6194.5 1539.34  6282.0 1546.77  6383.9 1550.09
#Mann=13,-1,0
  3705.4    0.07       0  3937.5   0.035       0  4084.7    0.07       0
  4200.1   0.035       0  4323.8    0.07       0  4507.9   0.035       0
  4973.1    0.07       0  5014.3   0.035       0  5501.9   0.035       0
  5629.4    0.07       0  5789.8   0.035       0  5963.2    0.07       0
  6000.0   0.035       0
Bank Sta=4973.1,5014.3
Exp/Cntr=0.3,0.1

Type RM Length L Ch R = 1,5083,494,494,494
BEGIN DESCRIPTION:
Mapping XS ef15d506
END DESCRIPTION:
XS GIS Cut Line= 3
      1658413.82      7010805.13      1659848.67      7010841.59
      1661169.77      7010943.01
#Sta/Elev= 30
  3558.4 1564.29  3619.6 1557.42  3809.7 1544.82  4089.8 1532.16  4226.5 1531.72
  4335.7 1532.20  4409.9 1524.90  4479.9 1505.86  4539.9 1485.24  4619.9 1465.78
  4750.4 1461.14  4862.6 1460.22  4872.1 1459.77  4970.0 1455.16  4979.4 1445.31
  4980.4 1444.81  5020.7 1445.31  5028.8 1445.74  5110.4 1472.35  5139.1 1477.90
  5144.1 1475.27  5190.6 1474.87  5269.6 1489.62  5441.4 1500.04  5661.2 1508.80
  5752.3 1509.85  5822.5 1505.45  5892.7 1515.01  6113.3 1527.94  6318.7 1543.96
#Mann=9,-1,0
  3558.4    0.07       0  4226.5   0.035       0  4335.7    0.07       0
  4750.4   0.035       0  4862.6    0.07       0  4872.1   0.035       0
  4979.4   0.035       0  5020.7   0.035       0  5028.8    0.07       0
Bank Sta=4979.4,5020.7
Exp/Cntr=0.3,0.1

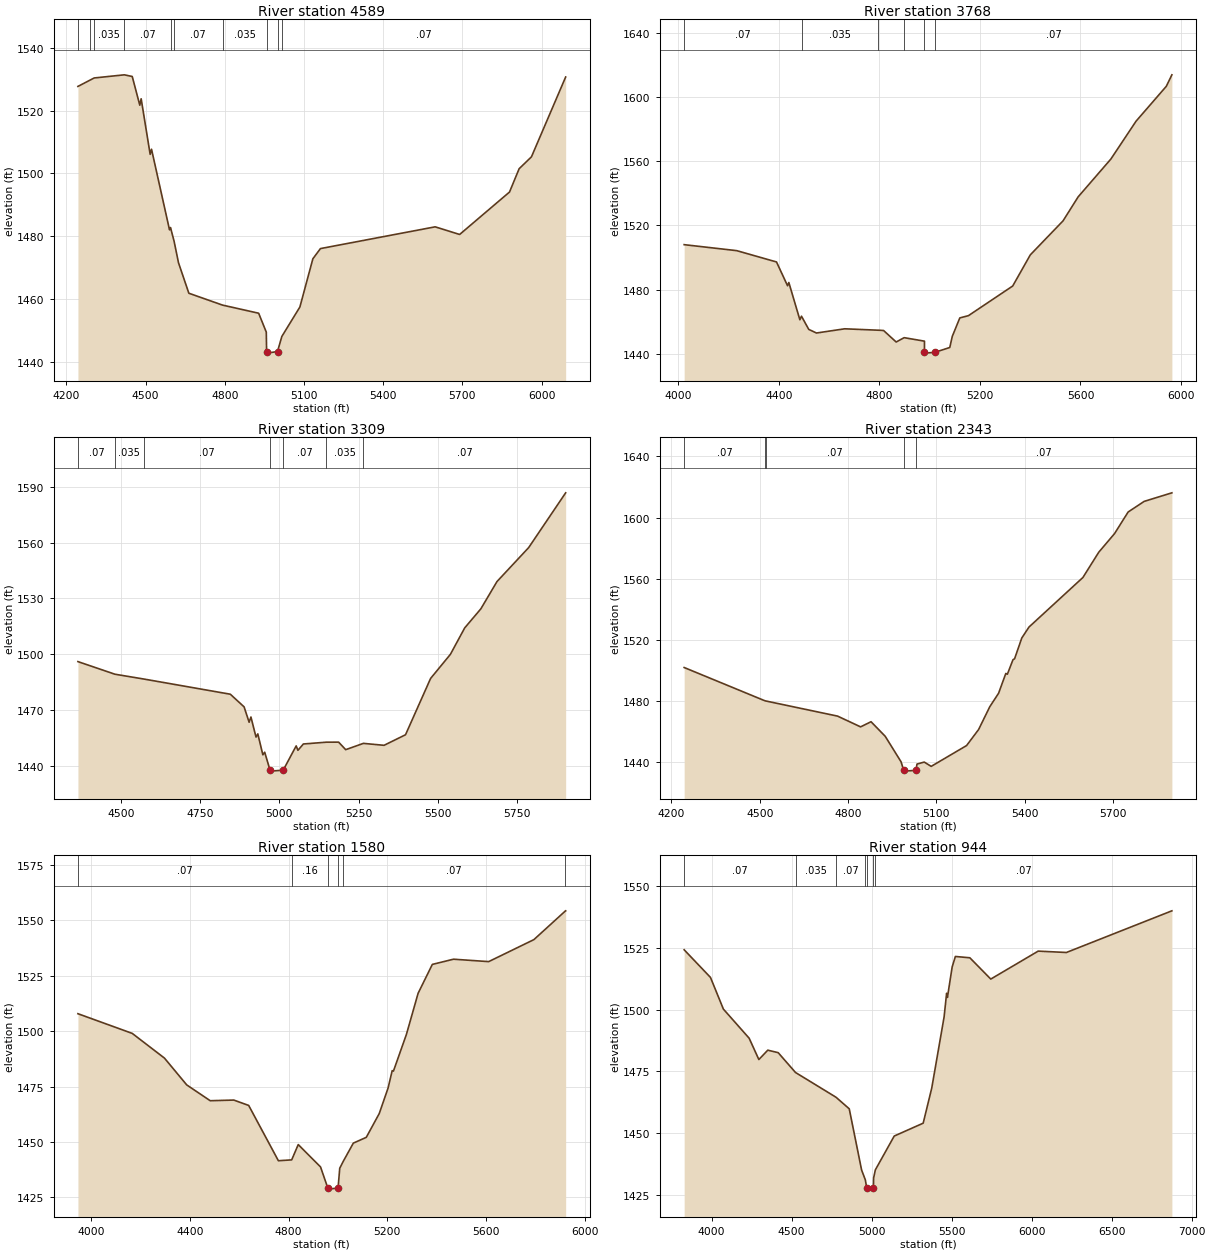
Type RM Length L Ch R = 1,4589,821,821,821
BEGIN DESCRIPTION:
Mapping XS 48338744
END DESCRIPTION:
XS GIS Cut Line= 3
      1659126.88      7011098.87      1659856.09      7011303.74
      1660915.10      7011564.15
#Sta/Elev= 30
  4243.4 1527.69  4288.0 1529.64  4305.0 1530.38  4419.2 1531.38  4449.2 1530.85
  4477.8 1521.72  4483.0 1523.76  4517.1 1506.09  4522.3 1507.71  4590.4 1482.08
  4594.2 1482.80  4607.8 1478.44  4624.5 1471.60  4663.7 1461.91  4791.2 1458.14
  4928.2 1455.55  4957.1 1449.54  4958.3 1443.36  4959.3 1442.86  4999.6 1443.36
  5016.0 1448.16  5084.4 1457.53  5133.6 1472.87  5162.3 1476.11  5597.0 1483.03
  5689.7 1480.60  5878.7 1494.10  5915.1 1501.51  5961.8 1505.30  6091.4 1530.69
#Mann=10,-1,0
  4243.4   0.035       0  4288.0    0.07       0  4305.0   0.035       0
  4419.2    0.07       0  4594.2   0.035       0  4607.8    0.07       0
  4791.2   0.035       0  4958.3   0.035       0  4999.6   0.035       0
  5016.0    0.07       0
Bank Sta=4958.3,4999.6
Exp/Cntr=0.3,0.1

Type RM Length L Ch R = 1,3768,459,459,459
BEGIN DESCRIPTION:
Mapping XS 69c3dc1c
END DESCRIPTION:
XS GIS Cut Line= 3
      1659300.57      7011744.72      1660255.39      7011953.05
      1661217.18      7012015.54
#Sta/Elev= 30
  4022.8 1507.96  4232.0 1504.23  4390.4 1497.18  4434.3 1482.36  4439.4 1484.37
  4483.3 1461.18  4489.8 1463.38  4518.6 1455.17  4549.3 1452.90  4661.9 1455.53
  4796.2 1454.65  4816.4 1454.48  4866.6 1447.30  4898.4 1450.00  4979.2 1447.83
  4979.3 1440.87  4980.3 1440.37  5020.7 1440.87  5079.9 1443.88  5089.9 1450.81
  5119.9 1462.31  5154.3 1463.73  5330.4 1482.20  5400.5 1501.62  5530.8 1522.81
  5590.9 1537.76  5721.2 1561.34  5821.4 1584.93  5941.7 1606.65  5963.9 1613.80
#Mann=6,-1,0
  4022.8    0.07       0  4489.8   0.035       0  4796.2    0.07       0
  4898.4   0.035       0  4979.3   0.035       0  5020.7    0.07       0
Bank Sta=4979.3,5020.7
Exp/Cntr=0.3,0.1

Type RM Length L Ch R = 1,3309,966,966,966
BEGIN DESCRIPTION:
Mapping XS 952d23f9
END DESCRIPTION:
XS GIS Cut Line= 3
      1659452.92      7011936.36      1660008.45      7012248.84
      1660820.06      7012639.45
#Sta/Elev= 30
  4365.1 1496.06  4481.9 1489.28  4572.9 1486.70  4845.7 1478.54  4889.1 1471.75
  4905.0 1463.49  4910.7 1466.30  4926.7 1455.52  4932.4 1457.22  4948.3 1445.99
  4954.1 1447.38  4971.0 1437.72  4972.0 1437.22  5012.4 1437.72  5053.4 1450.77
  5058.9 1448.40  5076.0 1451.80  5148.6 1452.77  5187.3 1452.79  5209.5 1448.75
  5265.3 1452.13  5330.5 1451.09  5398.2 1456.76  5477.3 1487.02  5539.7 1499.96
  5584.9 1514.18  5635.7 1524.40  5686.7 1539.08  5786.6 1557.32  5903.2 1586.74
#Mann=7,-1,0
  4365.1    0.07       0  4481.9   0.035       0  4572.9    0.07       0
  4971.0    0.07       0  5012.4    0.07       0  5148.6   0.035       0
  5265.3    0.07       0
Bank Sta=4971,5012.4
Exp/Cntr=0.3,0.1

Type RM Length L Ch R = 1,2343,763,763,763
BEGIN DESCRIPTION:
Mapping XS 05b30734
END DESCRIPTION:
XS GIS Cut Line= 3
      1659227.19      7011888.58      1659509.32      7012596.06
      1659834.83      7013429.38
#Sta/Elev= 30
  4243.3 1501.90  4516.5 1480.22  4520.7 1480.00  4764.3 1470.10  4842.5 1463.07
  4877.9 1466.43  4926.1 1456.90  4980.0 1440.17  4988.9 1434.61  4989.9 1434.11
  5030.3 1434.61  5034.1 1438.73  5058.6 1440.03  5082.2 1437.22  5202.4 1450.84
  5243.2 1461.32  5281.2 1476.25  5311.1 1485.07  5335.6 1498.01  5340.9 1497.51
  5360.0 1507.00  5365.4 1507.61  5389.9 1521.22  5414.4 1528.39  5597.5 1560.81
  5651.2 1577.32  5704.9 1589.51  5751.0 1603.64  5805.4 1610.58  5899.6 1616.19
#Mann=5,-1,0
  4243.3    0.07       0  4516.5   0.035       0  4520.7    0.07       0
  4988.9    0.07       0  5030.3    0.07       0
Bank Sta=4988.9,5030.3
Exp/Cntr=0.3,0.1

Type RM Length L Ch R = 1,1580,636,636,636
BEGIN DESCRIPTION:
Mapping XS b5eff874
END DESCRIPTION:
XS GIS Cut Line= 3
      1658758.45      7011688.91      1658840.91      7012747.97
      1659009.77      7013644.23
#Sta/Elev= 30
  3947.6 1507.81  4167.4 1498.94  4297.8 1487.81  4388.0 1475.73  4483.1 1468.60
  4578.6 1468.89  4638.8 1466.48  4759.1 1441.55  4812.9 1441.94  4839.4 1448.84
  4929.7 1438.76  4959.1 1429.26  4960.1 1428.76  5000.6 1429.26  5007.4 1438.16
  5021.1 1441.17  5062.4 1449.49  5114.9 1452.10  5167.3 1462.81  5203.2 1474.37
  5219.7 1482.15  5224.8 1481.95  5277.3 1498.48  5324.6 1517.00  5382.2 1530.02
  5467.8 1532.37  5610.3 1531.28  5793.4 1541.20  5920.4 1554.07  5921.9 1554.17
#Mann=6,-1,0
  3947.6    0.07       0  4812.9    0.16       0  4959.1    0.07       0
  5000.6    0.16       0  5021.1    0.07       0  5920.4   0.035       0
Bank Sta=4959.1,5000.6
Exp/Cntr=0.3,0.1

Type RM Length L Ch R = 1,944,658,658,658
BEGIN DESCRIPTION:
Mapping XS 37fc49d0
END DESCRIPTION:
XS GIS Cut Line= 3
      1658412.28      7011374.66      1658271.74      7012547.03
      1658467.73      7014403.35
#Sta/Elev= 30
  3829.1 1524.25  3993.6 1513.05  4074.2 1500.22  4235.3 1488.41  4295.8 1479.78
  4351.7 1483.57  4416.6 1482.56  4524.8 1474.53  4777.9 1464.50  4860.6 1459.81
  4937.9 1434.98  4961.0 1431.05  4969.9 1427.76  4970.9 1427.26  5011.5 1427.76
  5012.9 1431.81  5023.9 1435.09  5141.6 1448.77  5322.6 1453.99  5376.1 1468.22
  5453.3 1497.05  5468.9 1506.63  5474.0 1504.94  5503.6 1517.29  5523.7 1521.54
  5614.2 1521.01  5744.9 1512.38  6041.2 1523.71  6217.5 1523.16  6876.5 1540.04
#Mann=7,-1,0
  3829.1    0.07       0  4524.8   0.035       0  4777.9    0.07       0
  4961.0    0.16       0  4969.9    0.07       0  5011.5    0.16       0
  5023.9    0.07       0
Bank Sta=4969.9,5011.5
Exp/Cntr=0.3,0.1

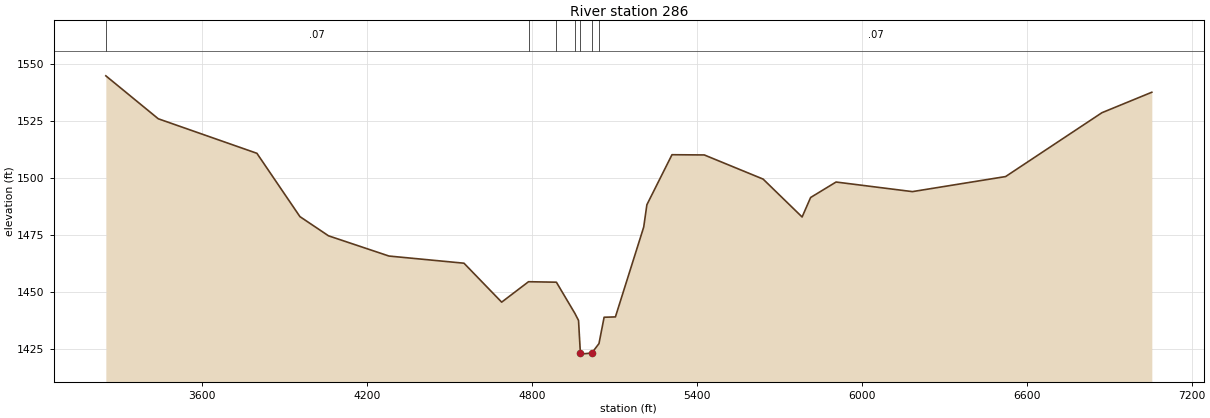
Type RM Length L Ch R = 1,286,0,0,0
BEGIN DESCRIPTION:
Mapping XS 651abec9
END DESCRIPTION:
XS GIS Cut Line= 3
      1658245.62      7011061.89      1657739.47      7012737.41
      1658224.46      7014734.25
#Sta/Elev= 30
  3249.7 1544.81  3440.5 1525.95  3799.3 1510.79  3955.8 1482.99  4059.9 1474.56
  4279.8 1465.68  4552.6 1462.54  4689.7 1445.44  4787.4 1454.41  4888.8 1454.20
  4956.3 1440.46  4969.3 1437.42  4976.0 1423.12  4977.0 1422.62  5017.6 1423.12
  5043.7 1427.24  5062.4 1438.81  5103.5 1438.96  5206.4 1478.38  5218.0 1488.21
  5309.3 1510.17  5426.8 1510.07  5640.8 1499.47  5782.7 1482.83  5813.6 1491.38
  5906.2 1498.18  6183.8 1493.97  6523.0 1500.58  6873.5 1528.62  7054.9 1537.60
#Mann=7,-1,0
  3249.7    0.07       0  4787.4    0.07       0  4888.8    0.16       0
  4956.3   0.033       0  4976.0   0.033       0  5017.6   0.033       0
  5043.7    0.07       0
Bank Sta=4976,5017.6
Exp/Cntr=0.3,0.1

Chan Stop Cuts=-1