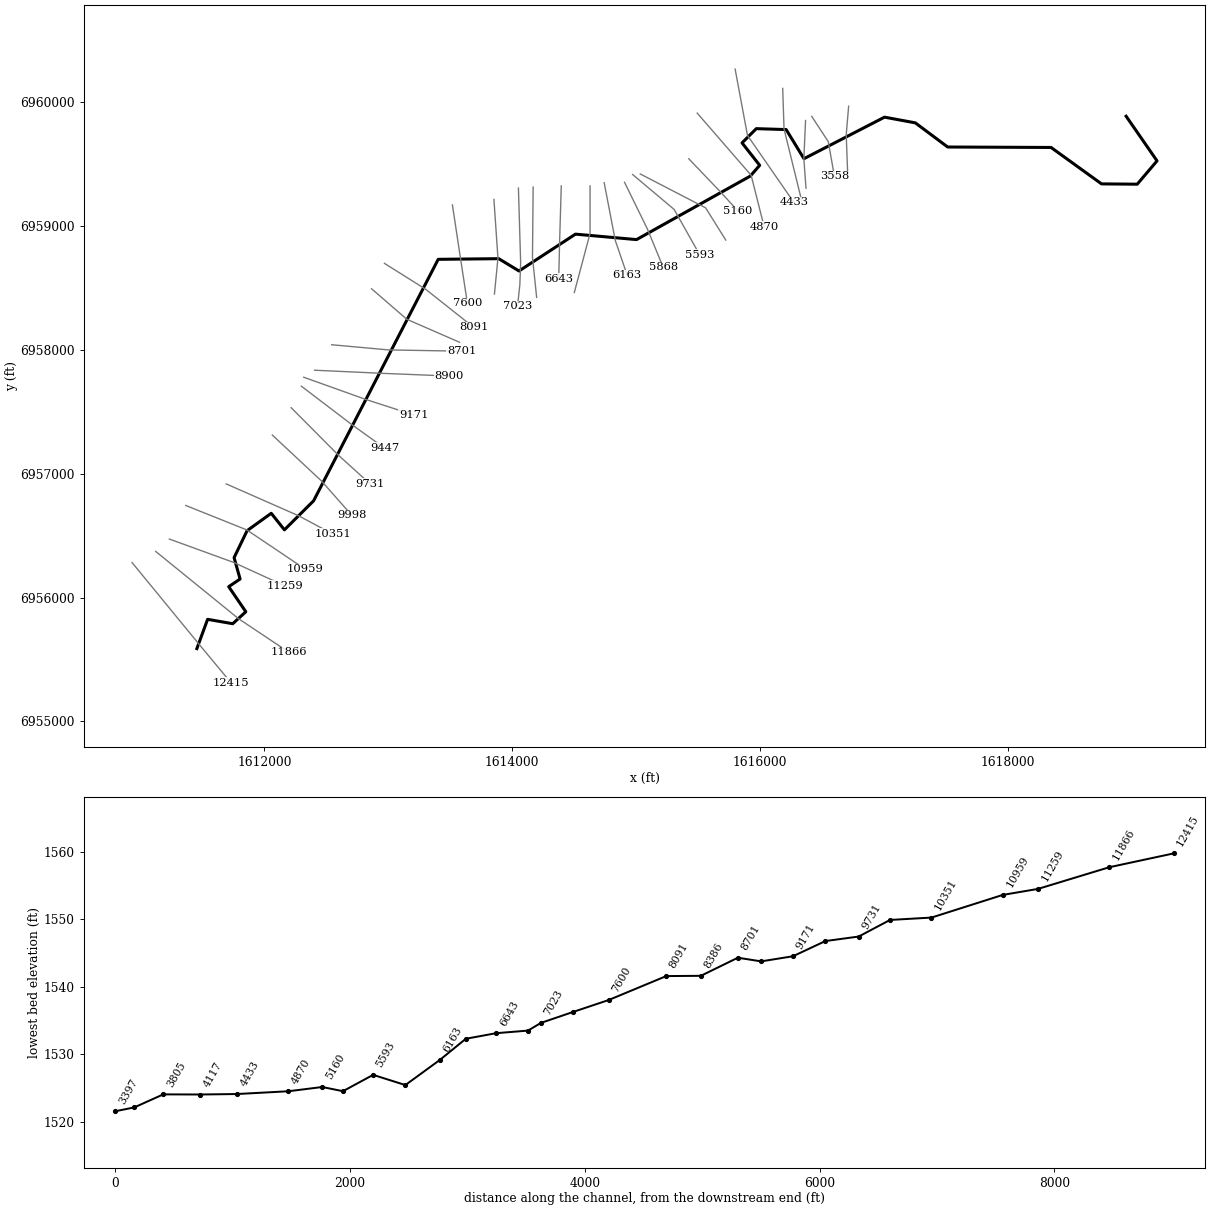
--- Flatrock Creek.prj (project) ---

Proj Title=Flatrock Creek Base Level Engineering
Current Plan=p01
Default Exp/Contr=0.3,0.1
English Units
Geom File=g01
Flow File=f01
Plan File=p01
BEGIN DESCRIPTION:
Flatrock Creek
END DESCRIPTION:

--- Flatrock Creek.p01 (plan) ---

Plan Title=Multiple Run
Short Identifier=Multiple
Geom File=g01
Flow File=f01
Subcritical Flow
K Sum by GR= 0
Std Step Tol= 0.01
Critical Tol= 0.01
Num of Std Step Trials= 20
Max Error Tol= 0.3
Flow Tol Ratio= 0.001
Split Flow NTrial= 30
Split Flow Tol= 0.02
Split Flow Ratio= 0.02
Log Output Level= 0
Friction Slope Method= 1
Unsteady Friction Slope Method= 2
Unsteady Bridges Friction Slope Method= 1
Parabolic Critical Depth
Global Vel Dist=  1 , 1 , 1
Global Log Level= 0
CheckData=True
Encroach Param= -1, 0, 0, 0
BEGIN DESCRIPTION:
Multiple Run
END DESCRIPTION:

--- Flatrock Creek.f01 (steady flow) ---

Flow Title=Multiple
Number of Profiles=7
Profile Names=10-year,25-year,50-year,1pct_min,100-year,1pct_plu,500-year
River Rch & RM= Flatrock Creek,Reach-1,12415
     337     472     585     360     719    1435    1101
River Rch & RM= Flatrock Creek,Reach-1,7023
     463     659     824     513    1023    2041    1596
River Rch & RM= Flatrock Creek,Reach-1,5336
     577     829    1044     653    1303    2600    2058
River Rch & RM= Flatrock Creek,Reach-1,3397
     578     827    1039     648    1293    2579    2029
Boundary for River Rch & Prof#=Flatrock Creek,Reach-1,1
Up Type=0
Dn Type=3
Dn Slope=0.005
Boundary for River Rch & Prof#=Flatrock Creek,Reach-1,2
Up Type=0
Dn Type=3
Dn Slope=0.005
Boundary for River Rch & Prof#=Flatrock Creek,Reach-1,3
Up Type=0
Dn Type=3
Dn Slope=0.005
Boundary for River Rch & Prof#=Flatrock Creek,Reach-1,4
Up Type=0
Dn Type=3
Dn Slope=0.005
Boundary for River Rch & Prof#=Flatrock Creek,Reach-1,5
Up Type=0
Dn Type=3
Dn Slope=0.005
Boundary for River Rch & Prof#=Flatrock Creek,Reach-1,6
Up Type=0
Dn Type=3
Dn Slope=0.005
Boundary for River Rch & Prof#=Flatrock Creek,Reach-1,7
Up Type=0
Dn Type=3
Dn Slope=0.005

--- Flatrock Creek.g01 (geometry) ---

Geom Title=Existing Conditions

River Reach=Flatrock Creek,Reach-1
Reach XY= 30
      1611455.00      6955588.00      1611541.56      6955824.47
      1611744.57      6955789.03      1611849.94      6955885.70
      1611712.02      6956088.20      1611803.79      6956150.01
      1611755.25      6956322.78      1611860.42      6956540.67
      1612055.22      6956681.00      1612161.44      6956547.16
      1612397.14      6956781.83      1613402.70      6958732.20
      1613891.14      6958737.46      1614055.00      6958638.00
      1614510.53      6958935.62      1615003.53      6958891.55
      1615921.75      6959404.64      1615997.48      6959491.56
      1615854.94      6959672.66      1615970.15      6959787.62
      1616211.21      6959780.20      1616354.75      6959544.98
      1617004.99      6959880.47      1617253.54      6959834.46
      1617514.65      6959639.36      1618349.07      6959635.75
      1618756.47      6959341.55      1619044.57      6959339.05
      1619204.45      6959527.36      1618955.00      6959888.00

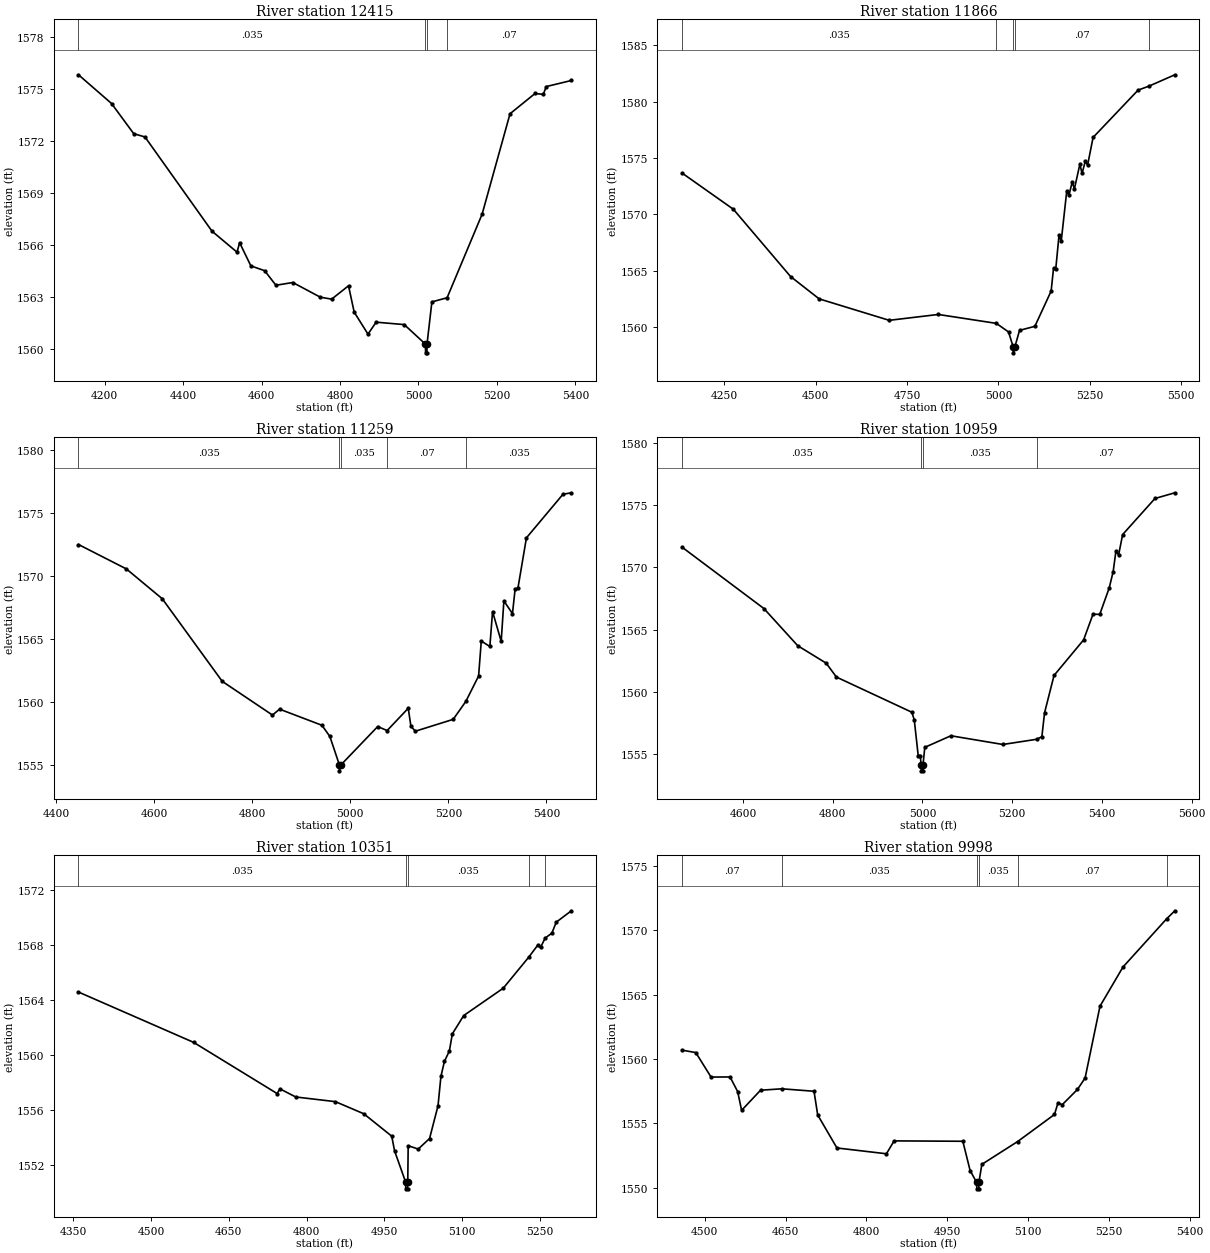
Type RM Length L Ch R = 1,12415,549,549,549
BEGIN DESCRIPTION:
Flatrock Creek 25.0
END DESCRIPTION:
XS GIS Cut Line= 3
      1610931.75      6956283.17      1611481.09      6955612.81
      1611730.02      6955312.97
#Sta/Elev= 30
  4133.3 1575.84  4217.6 1574.18  4274.1 1572.44  4302.8 1572.25  4473.7 1566.81
  4537.5 1565.60  4544.0 1566.15  4572.7 1564.81  4607.9 1564.53  4636.6 1563.69
  4679.6 1563.85  4750.0 1563.00  4778.7 1562.89  4821.7 1563.66  4836.1 1562.14
  4871.3 1560.87  4892.1 1561.56  4963.8 1561.42  5017.8 1560.29  5018.1 1559.79
  5021.6 1559.79  5021.8 1560.29  5034.2 1562.73  5073.0 1562.97  5162.2 1567.79
  5233.4 1573.59  5297.2 1574.76  5318.2 1574.71  5325.9 1575.16  5389.7 1575.51
#Mann=4,-1,0
  4133.3   0.035       0  5017.8   0.035       0  5021.8   0.035       0
  5073.0    0.07       0
Bank Sta=5017.8,5021.8
Exp/Cntr=0.3,0.1

Type RM Length L Ch R = 1,11866,607,607,607
BEGIN DESCRIPTION:
Mapping XS b6c47a52
END DESCRIPTION:
XS GIS Cut Line= 3
      1611122.45      6956372.98      1611793.03      6955828.27
      1612196.71      6955559.15
#Sta/Elev= 30
  4133.9 1573.67  4274.5 1570.46  4431.1 1564.50  4509.4 1562.52  4701.2 1560.62
  4835.5 1561.14  4994.4 1560.35  5027.8 1559.59  5040.8 1558.24  5041.0 1557.74
  5044.9 1558.24  5057.9 1559.73  5099.9 1560.09  5144.4 1563.21  5151.0 1565.24
  5157.0 1565.15  5166.0 1568.16  5172.0 1567.62  5187.1 1572.06  5193.1 1571.69
  5202.1 1572.87  5208.1 1572.26  5223.1 1574.45  5229.1 1573.63  5238.1 1574.74
  5244.1 1574.35  5259.2 1576.82  5382.4 1581.01  5413.4 1581.38  5483.0 1582.37
#Mann=5,-1,0
  4133.9   0.035       0  4994.4    0.07       0  5040.8    0.07       0
  5044.9    0.07       0  5413.4   0.035       0
Bank Sta=5040.8,5044.9
Exp/Cntr=0.3,0.1

Type RM Length L Ch R = 1,11259,300,300,300
BEGIN DESCRIPTION:
Mapping XS 3e048841
END DESCRIPTION:
XS GIS Cut Line= 3
      1611233.16      6956472.79      1611751.80      6956284.00
      1612164.10      6956095.21
#Sta/Elev= 30
  4445.4 1572.51  4543.1 1570.57  4616.3 1568.20  4738.6 1561.64  4841.1 1558.96
  4855.6 1559.43  4942.0 1558.15  4958.2 1557.26  4977.4 1555.03  4977.7 1554.53
  4981.5 1555.03  5055.8 1558.05  5075.0 1557.73  5118.1 1559.50  5123.6 1558.06
  5132.8 1557.68  5209.8 1558.62  5235.5 1560.04  5261.6 1562.06  5267.1 1564.84
  5284.6 1564.41  5290.1 1567.18  5307.7 1564.82  5313.2 1568.03  5330.7 1567.02
  5336.2 1569.00  5341.8 1569.03  5359.2 1573.04  5433.7 1576.50  5450.8 1576.62
#Mann=5,-1,0
  4445.4   0.035       0  4977.4   0.035       0  4981.5   0.035       0
  5075.0    0.07       0  5235.5   0.035       0
Bank Sta=4977.4,4981.5
Exp/Cntr=0.3,0.1

Type RM Length L Ch R = 1,10959,608,608,608
BEGIN DESCRIPTION:
Mapping XS d72474ba
END DESCRIPTION:
XS GIS Cut Line= 3
      1611365.49      6956744.08      1611858.14      6956546.58
      1612329.02      6956229.77
#Sta/Elev= 30
  4464.2 1571.63  4646.8 1566.69  4722.2 1563.70  4785.5 1562.30  4808.4 1561.18
  4976.6 1558.35  4981.9 1557.72  4990.6 1554.87  4995.0 1554.87  4997.2 1554.14
  4997.5 1553.64  5001.1 1553.64  5001.4 1554.14  5005.3 1555.53  5063.5 1556.46
  5179.3 1555.76  5255.0 1556.18  5266.2 1556.39  5272.2 1558.31  5293.3 1561.31
  5359.2 1564.17  5380.2 1566.24  5395.2 1566.22  5416.2 1568.34  5425.1 1569.66
  5431.2 1571.30  5437.2 1571.00  5446.2 1572.64  5518.2 1575.54  5562.5 1576.00
#Mann=4,-1,0
  4464.2   0.035       0  4997.2   0.035       0  5001.4   0.035       0
  5255.0    0.07       0
Bank Sta=4997.2,5001.4
Exp/Cntr=0.3,0.1

Type RM Length L Ch R = 1,10351,353,353,353
BEGIN DESCRIPTION:
Mapping XS 500af08f
END DESCRIPTION:
XS GIS Cut Line= 3
      1611691.95      6956918.24      1612275.24      6956661.31
      1612550.68      6956514.06
#Sta/Elev= 30
  4360.5 1564.59  4582.4 1560.93  4743.2 1557.21  4748.7 1557.55  4779.1 1556.96
  4855.6 1556.62  4910.2 1555.74  4964.1 1554.11  4969.6 1553.04  4990.8 1550.78
  4991.1 1550.28  4994.7 1550.28  4995.0 1550.78  4995.8 1553.42  5015.1 1553.17
  5037.0 1553.94  5053.3 1556.32  5058.9 1558.46  5065.6 1559.54  5075.2 1560.31
  5080.9 1561.55  5102.8 1562.88  5179.0 1564.87  5228.2 1567.13  5245.1 1567.98
  5250.8 1567.83  5259.8 1568.52  5272.7 1568.87  5281.1 1569.67  5310.2 1570.50
#Mann=5,-1,0
  4360.5   0.035       0  4990.8   0.035       0  4995.0   0.035       0
  5228.2    0.07       0  5259.8   0.035       0
Bank Sta=4990.8,4995
Exp/Cntr=0.3,0.1

Type RM Length L Ch R = 1,9998,267,267,267
BEGIN DESCRIPTION:
Mapping XS beab61e9
END DESCRIPTION:
XS GIS Cut Line= 3
      1612063.85      6957312.81      1612458.83      6956943.86
      1612706.23      6956663.91
#Sta/Elev= 30
  4458.0 1560.69  4483.6 1560.50  4511.9 1558.60  4547.1 1558.61  4561.2 1557.48
  4568.6 1556.02  4603.7 1557.58  4643.3 1557.69  4702.9 1557.50  4709.7 1555.66
  4745.4 1553.10  4837.2 1552.65  4851.4 1553.65  4978.9 1553.62  4992.4 1551.35
  5004.5 1550.43  5004.8 1549.93  5008.5 1549.93  5008.7 1550.43  5014.2 1551.83
  5080.6 1553.60  5148.9 1555.70  5155.5 1556.61  5163.1 1556.45  5191.5 1557.64
  5205.7 1558.53  5233.3 1564.10  5276.0 1567.14  5357.0 1570.88  5372.1 1571.50
#Mann=6,-1,0
  4458.0    0.07       0  4643.3   0.035       0  5004.5   0.035       0
  5008.7   0.035       0  5080.6    0.07       0  5357.0   0.035       0
Bank Sta=5004.5,5008.7
Exp/Cntr=0.3,0.1

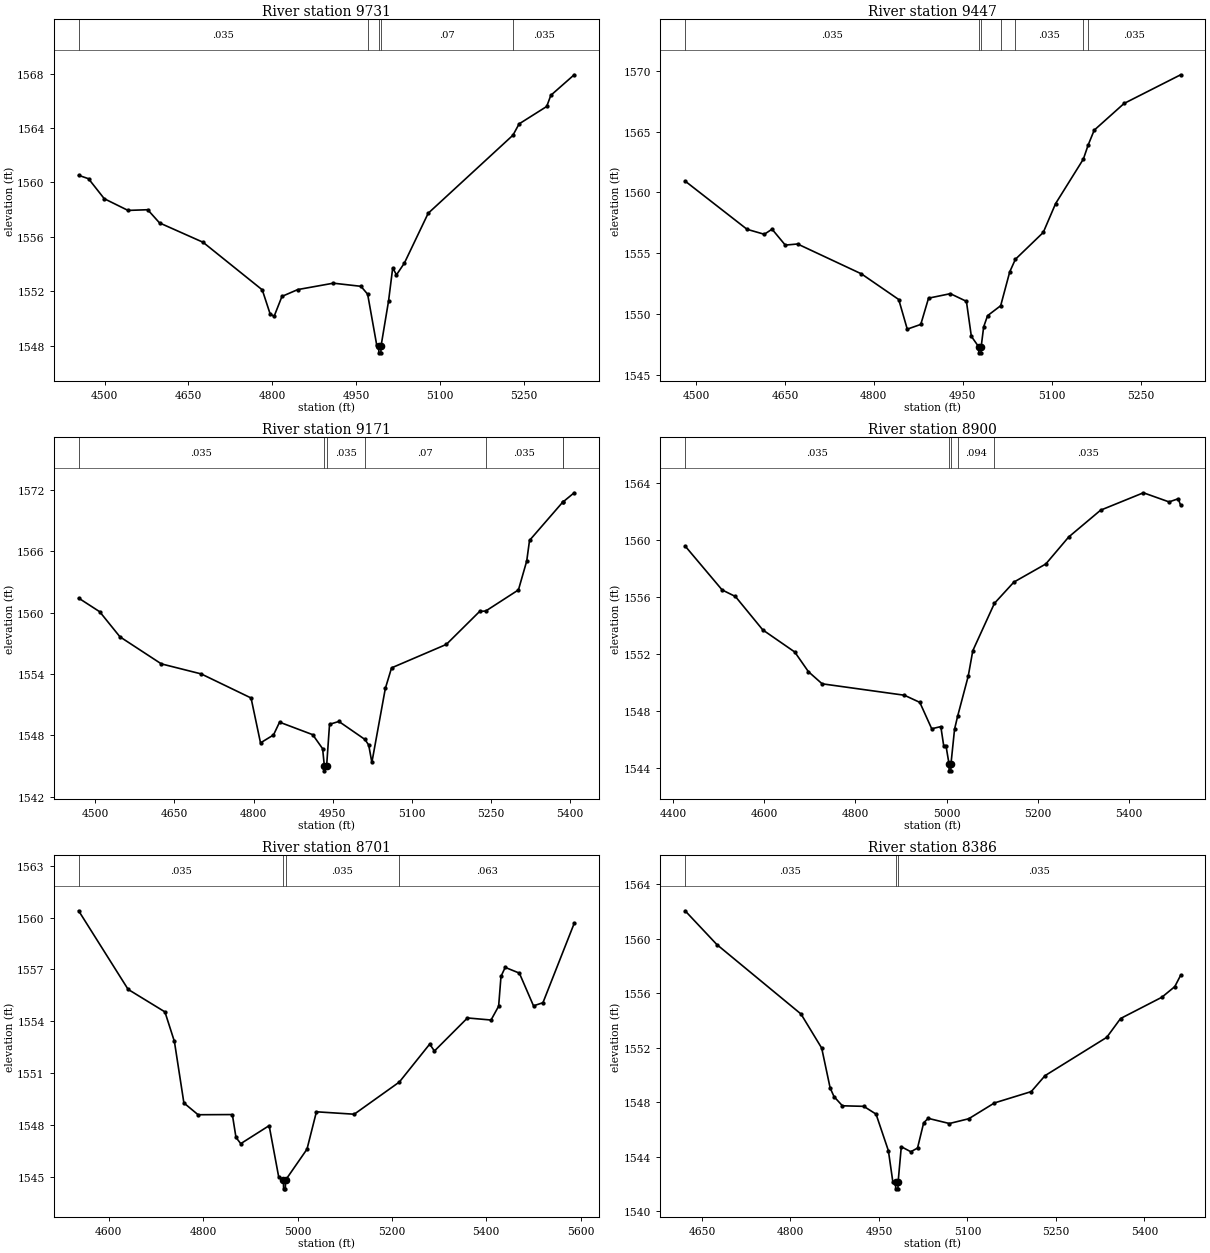
Type RM Length L Ch R = 1,9731,284,284,284
BEGIN DESCRIPTION:
Mapping XS 45446bff
END DESCRIPTION:
XS GIS Cut Line= 3
      1612215.89      6957533.85      1612597.81      6957149.76
      1612853.86      6956917.58
#Sta/Elev= 30
  4453.4 1560.52  4471.1 1560.27  4499.3 1558.80  4541.8 1557.94  4577.1 1557.99
  4598.3 1557.02  4676.1 1555.60  4782.2 1552.10  4796.3 1550.33  4803.4 1550.15
  4817.5 1551.62  4845.8 1552.12  4909.5 1552.59  4958.9 1552.36  4970.9 1551.78
  4987.2 1548.03  4990.7 1547.97  4990.9 1547.47  4994.6 1547.47  4994.9 1547.97
  5008.3 1551.27  5015.8 1553.72  5022.5 1553.20  5036.7 1554.07  5079.3 1557.73
  5231.1 1563.47  5242.1 1564.30  5291.5 1565.58  5298.9 1566.40  5340.7 1567.91
#Mann=5,-1,0
  4453.4   0.035       0  4970.9    0.07       0  4990.7    0.07       0
  4994.9    0.07       0  5231.1   0.035       0
Bank Sta=4990.7,4994.9
Exp/Cntr=0.3,0.1

Type RM Length L Ch R = 1,9447,276,276,276
BEGIN DESCRIPTION:
Mapping XS 1c4ccd3c
END DESCRIPTION:
XS GIS Cut Line= 3
      1612298.34      6957707.48      1612708.49      6957394.98
      1612968.89      6957208.36
#Sta/Elev= 30
  4481.6 1560.94  4586.1 1556.97  4615.2 1556.56  4628.3 1556.98  4650.6 1555.67
  4671.4 1555.76  4779.1 1553.30  4842.0 1551.19  4856.4 1548.75  4879.2 1549.14
  4892.3 1551.30  4929.1 1551.67  4956.2 1551.04  4964.5 1548.16  4976.9 1547.30
  4977.1 1546.80  4980.8 1546.80  4981.1 1547.30  4985.3 1548.94  4991.9 1549.86
  5014.0 1550.68  5029.3 1553.47  5038.8 1554.50  5085.8 1556.71  5106.7 1559.09
  5153.5 1562.75  5161.6 1563.91  5171.8 1565.13  5222.2 1567.33  5317.6 1569.69
#Mann=7,-1,0
  4481.6   0.035       0  4976.9   0.035       0  4981.1   0.035       0
  5014.0    0.07       0  5038.8   0.035       0  5153.5    0.07       0
  5161.6   0.035       0
Bank Sta=4976.9,4981.1
Exp/Cntr=0.3,0.1

Type RM Length L Ch R = 1,9171,271,271,271
BEGIN DESCRIPTION:
Mapping XS 50e5ee46
END DESCRIPTION:
XS GIS Cut Line= 3
      1612317.43      6957779.82      1612817.73      6957600.70
      1613205.45      6957475.28
#Sta/Elev= 30
  4468.6 1561.41  4508.5 1560.08  4546.9 1557.63  4625.3 1554.99  4700.8 1554.01
  4795.3 1551.66  4813.2 1547.28  4837.8 1548.05  4849.3 1549.30  4912.1 1548.08
  4930.9 1546.71  4934.1 1545.05  4934.4 1544.55  4938.5 1545.05  4944.0 1549.09
  4961.7 1549.37  5010.9 1547.62  5018.2 1547.07  5024.2 1545.37  5049.7 1552.59
  5061.5 1554.60  5165.3 1556.89  5228.4 1560.11  5240.0 1560.15  5301.9 1562.21
  5317.6 1565.03  5322.9 1567.04  5385.7 1570.77  5386.0 1570.78  5407.5 1571.69
#Mann=7,-1,0
  4468.6   0.035       0  4934.1   0.035       0  4938.5   0.035       0
  5010.9    0.07       0  5240.0   0.035       0  5385.7    0.07       0
  5386.0   0.035       0
Bank Sta=4934.1,4938.5
Exp/Cntr=0.3,0.1

Type RM Length L Ch R = 1,8900,199,199,199
BEGIN DESCRIPTION:
Mapping XS 3fec1719
END DESCRIPTION:
XS GIS Cut Line= 3
      1612404.85      6957836.53      1612972.52      6957810.49
      1613490.33      6957789.67
#Sta/Elev= 30
  4426.4 1559.55  4507.6 1556.47  4536.7 1556.01  4596.7 1553.67  4666.8 1552.12
  4696.8 1550.74  4726.9 1549.89  4907.1 1549.09  4941.0 1548.59  4967.1 1546.74
  4987.1 1546.89  4993.4 1545.55  4998.4 1545.55  5005.0 1544.29  5005.3 1543.79
  5009.1 1543.79  5009.4 1544.29  5017.2 1546.71  5023.8 1547.60  5047.2 1550.43
  5057.2 1552.21  5104.6 1555.53  5147.3 1557.02  5217.3 1558.29  5267.4 1560.18
  5337.4 1562.06  5431.3 1563.28  5487.5 1562.64  5507.6 1562.86  5512.9 1562.40
#Mann=5,-1,0
  4426.4   0.035       0  5005.0   0.035       0  5009.4   0.035       0
  5023.8   0.094       0  5104.6   0.035       0
Bank Sta=5005,5009.4
Exp/Cntr=0.3,0.1

Type RM Length L Ch R = 1,8701,315,315,315
BEGIN DESCRIPTION:
Mapping XS a080f458
END DESCRIPTION:
XS GIS Cut Line= 3
      1612542.86      6958042.26      1613001.17      6958000.60
      1613591.18      6957990.20
#Sta/Elev= 30
  4536.1 1560.39  4641.0 1555.85  4719.0 1554.55  4739.1 1552.84  4759.2 1549.29
  4789.3 1548.61  4861.9 1548.62  4869.6 1547.30  4879.7 1546.94  4939.9 1547.98
  4960.0 1545.04  4970.2 1544.83  4970.5 1544.33  4974.3 1544.33  4974.6 1544.83
  5020.1 1546.62  5040.1 1548.78  5120.2 1548.64  5215.9 1550.50  5280.2 1552.69
  5290.2 1552.29  5360.2 1554.20  5410.2 1554.08  5426.3 1554.88  5431.3 1556.60
  5440.2 1557.12  5470.2 1556.79  5500.2 1554.90  5520.2 1555.08  5586.4 1559.66
#Mann=4,-1,0
  4536.1   0.035       0  4970.2   0.035       0  4974.6   0.035       0
  5215.9   0.063       0
Bank Sta=4970.2,4974.6
Exp/Cntr=0.3,0.1

Type RM Length L Ch R = 1,8386,295,295,295
BEGIN DESCRIPTION:
Mapping XS 2342a440
END DESCRIPTION:
XS GIS Cut Line= 3
      1612864.91      6958494.49      1613149.61      6958247.99
      1613574.11      6958062.60
#Sta/Elev= 30
  4621.5 1562.04  4675.4 1559.56  4817.9 1554.47  4853.0 1551.97  4867.3 1549.05
  4873.9 1548.41  4888.1 1547.74  4924.3 1547.70  4945.1 1547.13  4966.0 1544.45
  4973.6 1542.15  4978.1 1542.15  4978.4 1541.65  4982.2 1541.65  4982.5 1542.15
  4987.9 1544.74  5004.0 1544.37  5015.4 1544.64  5025.8 1546.49  5033.4 1546.82
  5069.4 1546.44  5102.2 1546.79  5145.8 1547.95  5208.1 1548.78  5231.5 1549.95
  5336.1 1552.76  5359.5 1554.14  5429.5 1555.70  5451.4 1556.48  5461.3 1557.31
#Mann=3,-1,0
  4621.5   0.035       0  4978.1   0.035       0  4982.5   0.035       0
Bank Sta=4978.1,4982.5
Exp/Cntr=0.3,0.1

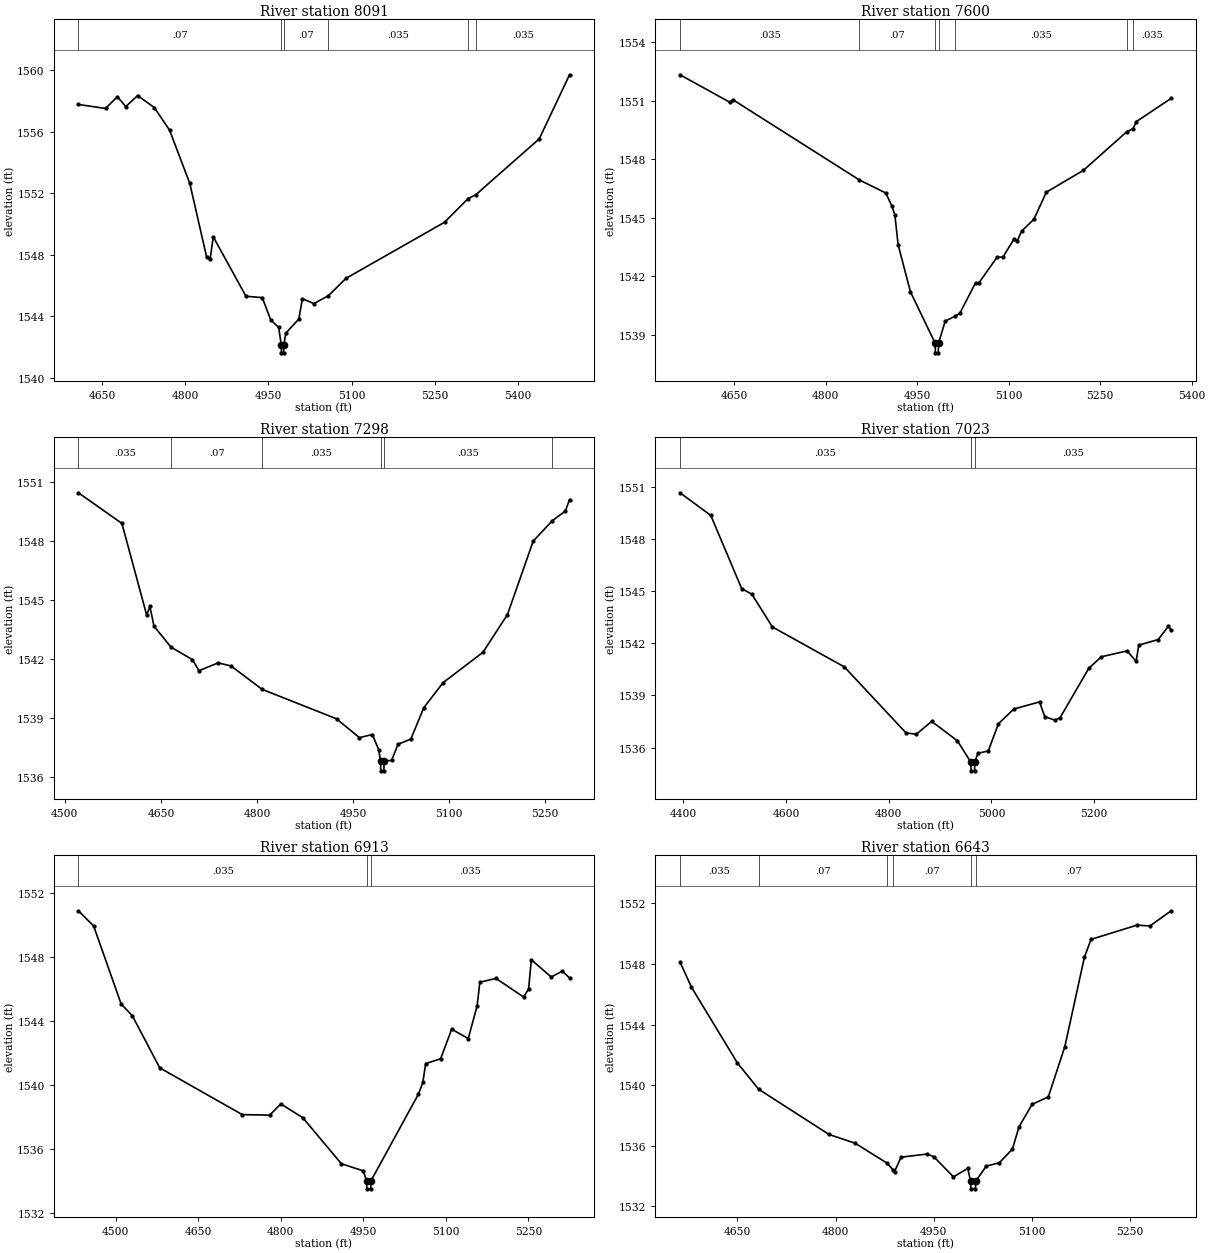
Type RM Length L Ch R = 1,8091,491,491,491
BEGIN DESCRIPTION:
Mapping XS 9d61851e
END DESCRIPTION:
XS GIS Cut Line= 3
      1612969.07      6958699.37      1613300.65      6958491.05
      1613687.82      6958183.74
#Sta/Elev= 30
  4607.3 1557.76  4656.3 1557.50  4677.5 1558.27  4692.8 1557.62  4714.0 1558.34
  4744.2 1557.56  4771.7 1556.09  4808.2 1552.63  4838.7 1547.82  4844.7 1547.68
  4850.6 1549.15  4909.5 1545.29  4938.9 1545.20  4954.3 1543.74  4968.6 1543.26
  4973.2 1542.11  4973.5 1541.61  4977.4 1541.61  4977.7 1542.11  4981.4 1542.89
  5004.9 1543.81  5011.3 1545.13  5032.1 1544.81  5058.4 1545.33  5089.8 1546.45
  5267.7 1550.10  5310.0 1551.63  5324.4 1551.90  5438.5 1555.52  5493.2 1559.69
#Mann=6,-1,0
  4607.3    0.07       0  4973.2    0.07       0  4977.7    0.07       0
  5058.4   0.035       0  5310.0    0.07       0  5324.4   0.035       0
Bank Sta=4973.2,4977.7
Exp/Cntr=0.3,0.1

Type RM Length L Ch R = 1,7600,302,302,302
BEGIN DESCRIPTION:
Mapping XS aee3ab42
END DESCRIPTION:
XS GIS Cut Line= 3
      1613517.48      6959171.36      1613582.59      6958740.35
      1613638.59      6958375.73
#Sta/Elev= 30
  4561.5 1552.34  4643.0 1550.93  4648.1 1551.06  4855.3 1546.94  4898.6 1546.27
  4908.4 1545.62  4913.5 1545.15  4918.9 1543.61  4939.1 1541.19  4979.5 1538.56
  4980.0 1538.06  4984.7 1538.06  4985.1 1538.56  4996.1 1539.69  5012.2 1539.94
  5020.0 1540.09  5045.8 1541.66  5050.8 1541.63  5080.7 1542.96  5090.8 1542.99
  5109.0 1543.91  5114.1 1543.80  5121.2 1544.31  5141.4 1544.92  5161.7 1546.31
  5222.4 1547.43  5293.4 1549.41  5304.1 1549.58  5309.0 1549.93  5366.3 1551.13
#Mann=7,-1,0
  4561.5   0.035       0  4855.3    0.07       0  4979.5    0.07       0
  4985.1    0.07       0  5012.2   0.035       0  5293.4    0.07       0
  5304.1   0.035       0
Bank Sta=4979.5,4985.1
Exp/Cntr=0.3,0.1

Type RM Length L Ch R = 1,7298,275,275,275
BEGIN DESCRIPTION:
Mapping XS 2b6f31a3
END DESCRIPTION:
XS GIS Cut Line= 3
      1613852.45      6959215.71      1613885.00      6958741.76
      1613856.50      6958451.53
#Sta/Elev= 30
  4521.2 1550.46  4589.1 1548.90  4627.8 1544.23  4632.8 1544.67  4639.2 1543.67
  4665.7 1542.60  4699.3 1541.96  4709.4 1541.40  4739.4 1541.80  4759.5 1541.64
  4808.0 1540.45  4924.1 1538.95  4959.9 1537.99  4980.0 1538.15  4990.0 1537.38
  4992.8 1536.80  4993.3 1536.30  4998.0 1536.30  4998.4 1536.80  5010.1 1536.83
  5020.1 1537.65  5040.2 1537.92  5060.3 1539.51  5090.5 1540.79  5152.8 1542.34
  5191.0 1544.26  5231.2 1548.00  5261.1 1549.04  5281.4 1549.53  5287.9 1550.11
#Mann=6,-1,0
  4521.2   0.035       0  4665.7    0.07       0  4808.0   0.035       0
  4992.8   0.035       0  4998.4   0.035       0  5261.1    0.07       0
Bank Sta=4992.8,4998.4
Exp/Cntr=0.3,0.1

Type RM Length L Ch R = 1,7023,110,110,110
BEGIN DESCRIPTION:
Mapping XS 98824590
END DESCRIPTION:
XS GIS Cut Line= 4
      1614050.15      6959307.91      1614068.27      6958701.78
      1614061.65      6958526.92      1614043.00      6958352.80
#Sta/Elev= 30
  4393.6 1550.64  4453.5 1549.34  4513.6 1545.14  4533.6 1544.81  4573.6 1542.93
  4713.6 1540.64  4833.7 1536.85  4853.7 1536.77  4883.7 1537.51  4933.7 1536.40
  4959.9 1535.17  4960.4 1534.67  4967.2 1534.67  4967.7 1535.17  4973.8 1535.68
  4993.8 1535.81  5013.8 1537.38  5043.8 1538.22  5093.8 1538.63  5103.9 1537.78
  5123.9 1537.58  5133.9 1537.73  5189.7 1540.56  5214.1 1541.22  5264.4 1541.56
  5281.9 1540.95  5287.0 1541.89  5324.8 1542.21  5344.9 1542.98  5350.1 1542.75
#Mann=3,-1,0
  4393.6   0.035       0  4959.9   0.035       0  4967.7   0.035       0
Bank Sta=4959.9,4967.7
Exp/Cntr=0.3,0.1

Type RM Length L Ch R = 1,6913,270,270,270
BEGIN DESCRIPTION:
Mapping XS 3aaa6a08
END DESCRIPTION:
XS GIS Cut Line= 3
      1614169.07      6959315.75      1614163.65      6958748.27
      1614197.28      6958424.92
#Sta/Elev= 30
  4432.3 1550.88  4460.0 1549.93  4510.0 1545.06  4530.1 1544.34  4580.1 1541.08
  4730.1 1538.16  4780.1 1538.13  4800.1 1538.83  4840.1 1537.97  4910.1 1535.10
  4950.1 1534.65  4956.1 1534.03  4956.6 1533.53  4963.5 1533.53  4964.0 1534.03
  5050.3 1539.44  5058.3 1540.17  5063.3 1541.34  5090.6 1541.65  5110.7 1543.49
  5140.8 1542.91  5156.9 1544.94  5161.9 1546.42  5191.1 1546.66  5241.4 1545.50
  5250.4 1545.99  5255.5 1547.82  5291.6 1546.75  5311.7 1547.11  5324.9 1546.69
#Mann=3,-1,0
  4432.3   0.035       0  4956.1   0.035       0  4964.0   0.035       0
Bank Sta=4956.1,4964
Exp/Cntr=0.3,0.1

Type RM Length L Ch R = 1,6643,260,260,260
BEGIN DESCRIPTION:
Mapping XS ddbb8799
END DESCRIPTION:
XS GIS Cut Line= 3
      1614396.07      6959325.46      1614383.05      6958889.26
      1614375.45      6958575.65
#Sta/Elev= 30
  4562.4 1548.13  4579.9 1546.46  4649.9 1541.47  4682.4 1539.73  4790.0 1536.74
  4830.0 1536.16  4878.4 1534.85  4887.6 1534.41  4890.0 1534.29  4900.0 1535.24
  4940.0 1535.45  4950.0 1535.27  4980.0 1533.94  5001.9 1534.50  5006.1 1533.65
  5006.6 1533.15  5013.5 1533.15  5014.0 1533.65  5030.1 1534.65  5050.1 1534.87
  5070.1 1535.78  5080.1 1537.24  5100.1 1538.73  5124.9 1539.22  5150.1 1542.54
  5180.1 1548.46  5190.1 1549.62  5260.1 1550.56  5280.1 1550.51  5312.5 1551.51
#Mann=6,-1,0
  4562.4   0.035       0  4682.4    0.07       0  4878.4   0.035       0
  4887.6    0.07       0  5006.1    0.07       0  5014.0    0.07       0
Bank Sta=5006.1,5014
Exp/Cntr=0.3,0.1

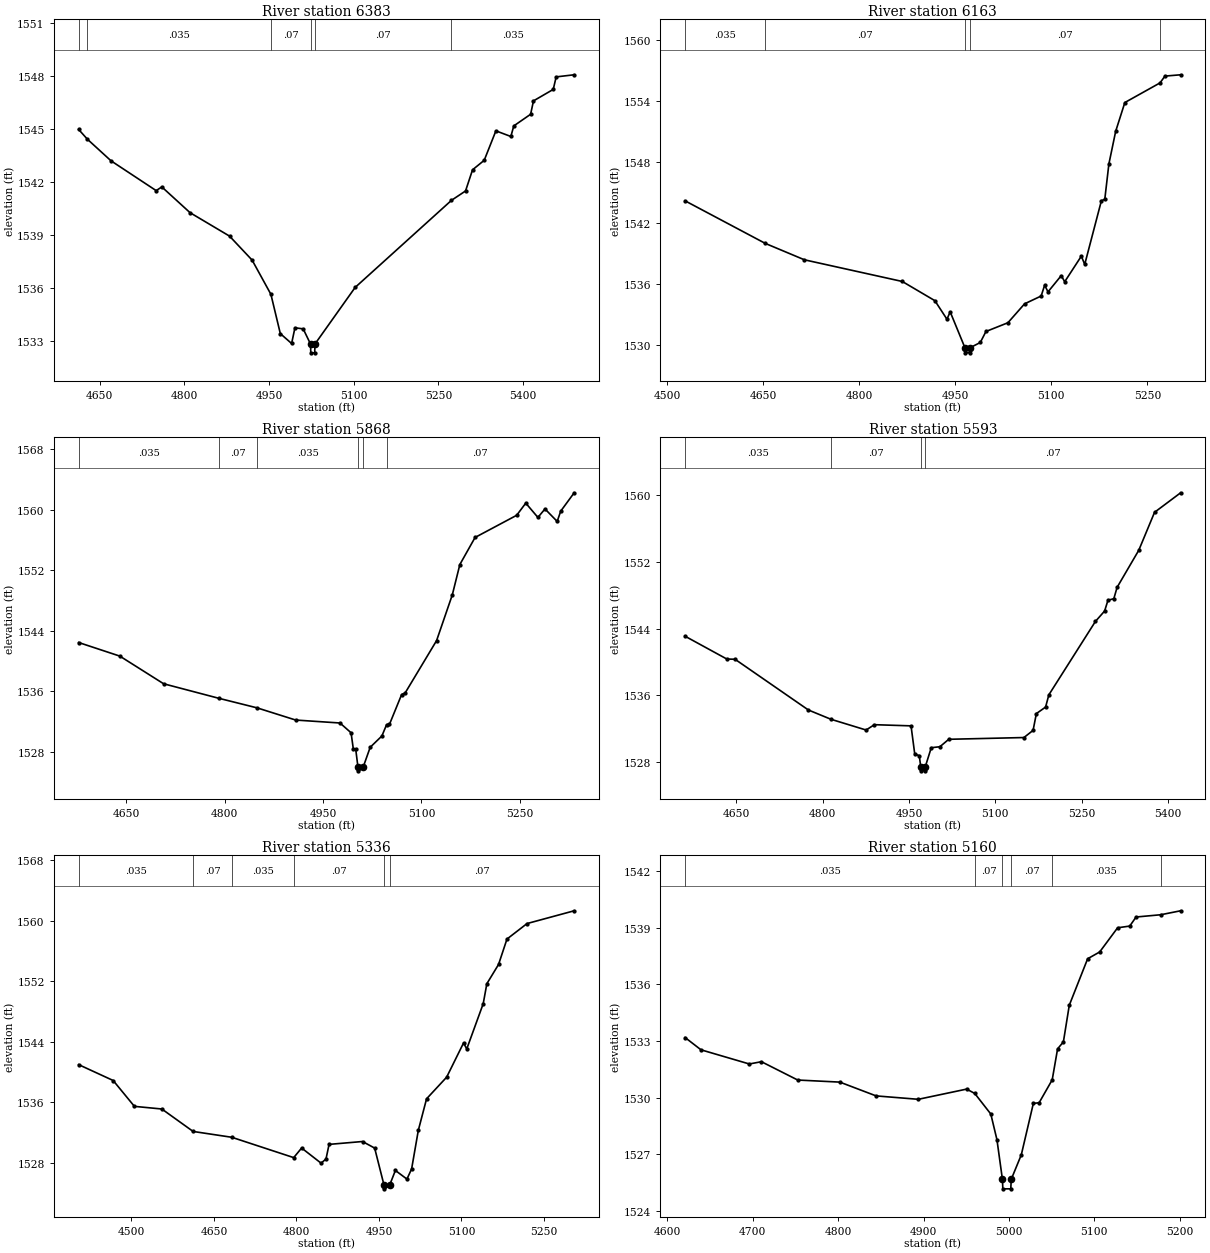
Type RM Length L Ch R = 1,6383,220,220,220
BEGIN DESCRIPTION:
Mapping XS 838314cb
END DESCRIPTION:
XS GIS Cut Line= 3
      1614628.27      6959325.44      1614628.27      6958941.34
      1614501.33      6958463.93
#Sta/Elev= 30
  4612.5 1544.99  4628.2 1544.43  4669.9 1543.21  4749.9 1541.52  4759.9 1541.73
  4809.9 1540.27  4879.9 1538.94  4919.9 1537.58  4953.2 1535.64  4969.9 1533.41
  4989.9 1532.85  4995.8 1533.74  5010.4 1533.68  5023.4 1532.82  5023.9 1532.32
  5030.8 1532.32  5031.3 1532.82  5102.5 1536.03  5273.2 1540.97  5298.1 1541.50
  5310.5 1542.70  5331.2 1543.24  5351.9 1544.91  5378.4 1544.59  5383.6 1545.19
  5413.4 1545.85  5418.5 1546.61  5453.5 1547.26  5458.7 1547.97  5490.6 1548.09
#Mann=6,-1,0
  4612.5    0.07       0  4628.2   0.035       0  4953.2    0.07       0
  5023.4    0.07       0  5031.3    0.07       0  5273.2   0.035       0
Bank Sta=5023.4,5031.3
Exp/Cntr=0.3,0.1

Type RM Length L Ch R = 1,6163,295,295,295
BEGIN DESCRIPTION:
Mapping XS 33c94ac7
END DESCRIPTION:
XS GIS Cut Line= 3
      1614742.42      6959350.93      1614831.40      6958886.51
      1614928.73      6958602.07
#Sta/Elev= 30
  4528.4 1544.15  4653.7 1539.96  4714.7 1538.35  4867.4 1536.22  4918.3 1534.33
  4937.1 1532.51  4942.2 1533.23  4965.2 1529.70  4965.7 1529.20  4972.7 1529.20
  4973.2 1529.70  4989.2 1530.22  4998.0 1531.30  5032.3 1532.16  5058.3 1534.02
  5084.2 1534.79  5089.6 1535.85  5094.9 1535.20  5115.6 1536.80  5120.9 1536.19
  5146.9 1538.71  5152.2 1537.90  5178.2 1544.16  5183.5 1544.30  5189.9 1547.78
  5200.5 1550.99  5214.8 1553.82  5269.7 1555.75  5277.4 1556.42  5301.9 1556.55
#Mann=5,-1,0
  4528.4   0.035       0  4653.7    0.07       0  4965.2    0.07       0
  4973.2    0.07       0  5269.7    0.16       0
Bank Sta=4965.2,4973.2
Exp/Cntr=0.3,0.1

Type RM Length L Ch R = 1,5868,275,275,275
BEGIN DESCRIPTION:
Mapping XS 09dbf430
END DESCRIPTION:
XS GIS Cut Line= 3
      1614906.49      6959354.39      1615091.38      6958976.79
      1615218.99      6958666.87
#Sta/Elev= 30
  4577.3 1542.44  4640.1 1540.64  4706.9 1536.98  4791.0 1535.06  4849.5 1533.79
  4908.3 1532.18  4975.8 1531.79  4992.7 1530.50  4996.2 1528.32  4999.8 1528.32
  5003.2 1525.96  5003.7 1525.46  5011.2 1525.96  5021.9 1528.58  5039.7 1530.07
  5046.9 1531.57  5051.3 1531.62  5069.8 1535.55  5075.2 1535.77  5123.1 1542.69
  5147.1 1548.75  5158.6 1552.76  5181.8 1556.34  5245.2 1559.27  5259.1 1560.88
  5277.6 1558.99  5288.4 1560.11  5307.0 1558.46  5312.4 1559.82  5332.9 1562.25
#Mann=6,-1,0
  4577.3   0.035       0  4791.0    0.07       0  4849.5   0.035       0
  5003.2   0.035       0  5011.2   0.035       0  5046.9    0.07       0
Bank Sta=5003.2,5011.2
Exp/Cntr=0.3,0.1

Type RM Length L Ch R = 1,5593,257,257,257
BEGIN DESCRIPTION:
Mapping XS cfdfe2ef
END DESCRIPTION:
XS GIS Cut Line= 3
      1614971.80      6959417.23      1615307.06      6959135.13
      1615514.33      6958767.25
#Sta/Elev= 30
  4561.4 1543.10  4633.8 1540.37  4648.1 1540.34  4775.5 1534.26  4814.6 1533.15
  4875.7 1531.86  4890.0 1532.50  4953.7 1532.36  4960.2 1528.95  4968.0 1528.80
  4970.5 1527.47  4971.0 1526.97  4978.0 1526.97  4978.5 1527.47  4988.8 1529.74
  5003.8 1529.86  5019.2 1530.75  5149.7 1530.96  5165.6 1531.82  5171.3 1533.83
  5187.3 1534.61  5193.0 1536.08  5273.9 1544.88  5289.8 1546.12  5295.6 1547.41
  5305.8 1547.60  5311.5 1548.96  5349.1 1553.40  5376.5 1557.95  5421.8 1560.29
#Mann=4,-1,0
  4561.4   0.035       0  4814.6    0.07       0  4970.5    0.07       0
  4978.5    0.07       0
Bank Sta=4970.5,4978.5
Exp/Cntr=0.3,0.1

Type RM Length L Ch R = 1,5336,176,176,176
BEGIN DESCRIPTION:
Mapping XS 22893cd7
END DESCRIPTION:
XS GIS Cut Line= 3
      1615033.66      6959421.57      1615560.97      6959148.15
      1615723.74      6958887.71
#Sta/Elev= 30
  4404.0 1540.98  4466.8 1538.88  4505.4 1535.46  4555.3 1535.11  4612.2 1532.14
  4682.5 1531.37  4795.1 1528.68  4809.5 1529.95  4844.8 1527.95  4853.8 1528.49
  4859.4 1530.43  4920.2 1530.81  4942.3 1529.94  4959.3 1525.05  4959.8 1524.55
  4969.6 1525.05  4980.0 1526.98  5001.0 1525.84  5009.5 1527.18  5021.7 1532.29
  5036.7 1536.46  5073.2 1539.32  5103.9 1543.84  5109.8 1543.06  5139.7 1549.04
  5146.3 1551.68  5167.6 1554.23  5182.9 1557.59  5219.4 1559.64  5305.1 1561.33
#Mann=6,-1,0
  4404.0   0.035       0  4612.2    0.07       0  4682.5   0.035       0
  4795.1    0.07       0  4959.3    0.07       0  4969.6    0.07       0
Bank Sta=4959.3,4969.6
Exp/Cntr=0.3,0.1

Type RM Length L Ch R = 1,5160,290,290,290
BEGIN DESCRIPTION:
Mapping XS 22d8292a
END DESCRIPTION:
XS GIS Cut Line= 3
      1615425.14      6959544.40      1615686.40      6959270.98
      1615822.67      6959121.69
#Sta/Elev= 30
  4620.8 1533.18  4639.4 1532.53  4696.0 1531.78  4710.2 1531.90  4752.7 1530.93
  4802.0 1530.82  4844.5 1530.09  4893.9 1529.91  4950.5 1530.45  4960.0 1530.22
  4978.8 1529.13  4986.0 1527.77  4992.4 1525.67  4992.9 1525.17  5002.2 1525.17
  5002.7 1525.67  5014.5 1526.97  5028.6 1529.69  5035.4 1529.73  5050.7 1530.94
  5057.0 1532.58  5063.8 1532.95  5070.7 1534.89  5092.2 1537.35  5106.3 1537.71
  5127.3 1538.99  5141.5 1539.08  5148.9 1539.56  5177.8 1539.68  5201.1 1539.89
#Mann=6,-1,0
  4620.8   0.035       0  4960.0    0.07       0  4992.4    0.07       0
  5002.7    0.07       0  5050.7   0.035       0  5177.8    0.07       0
Bank Sta=4992.4,5002.7
Exp/Cntr=0.3,0.1

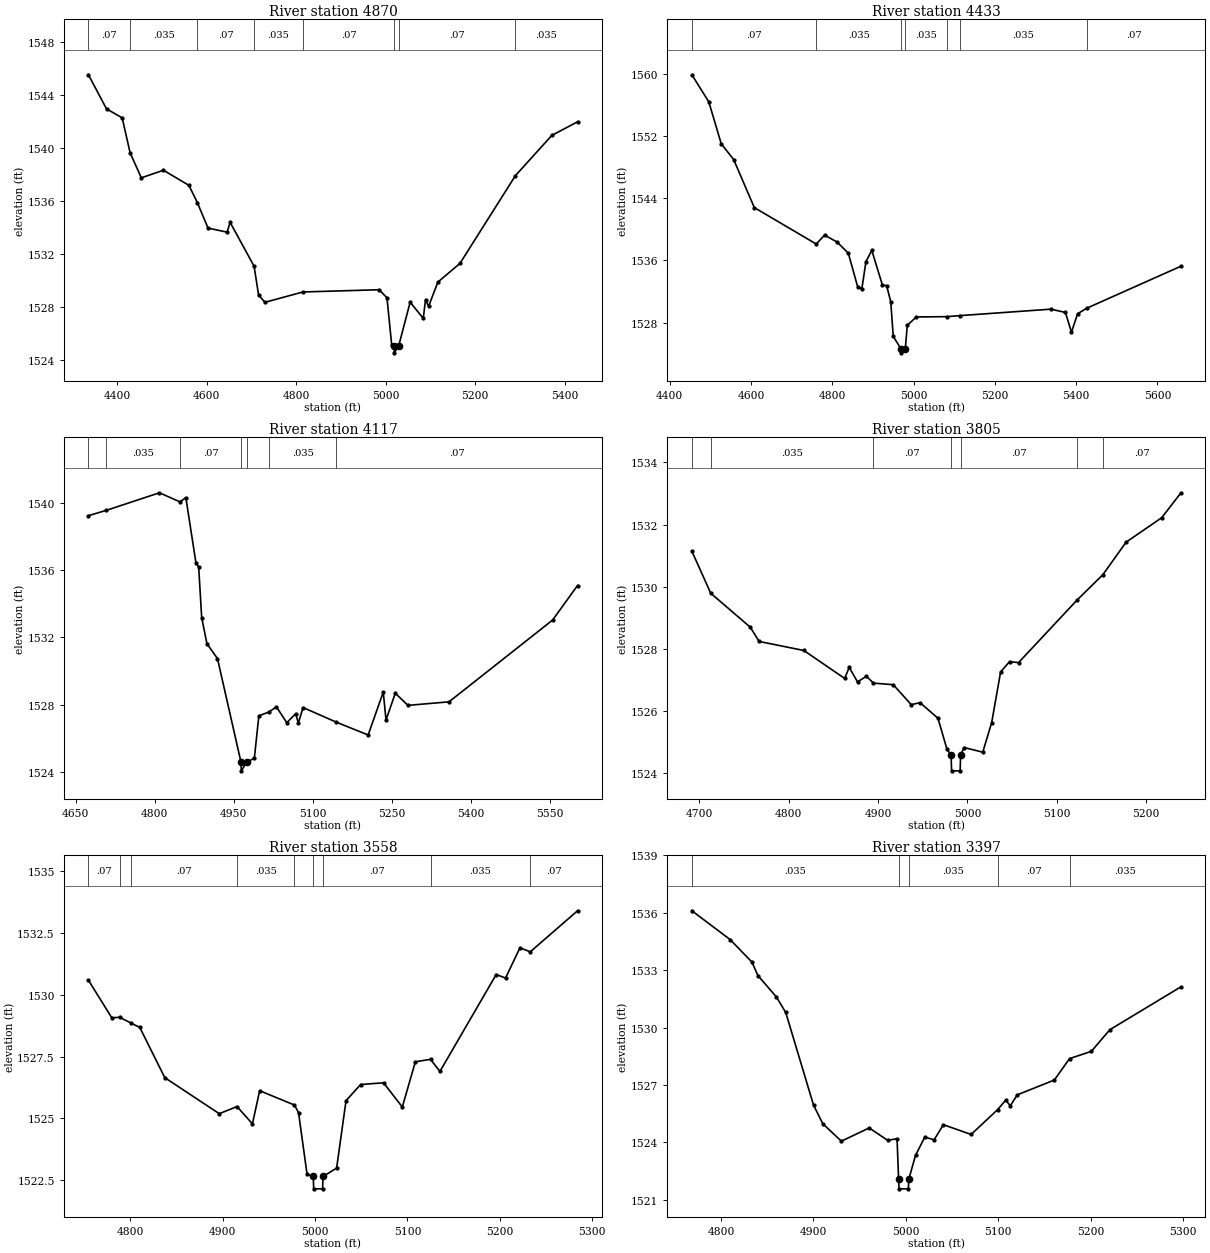
Type RM Length L Ch R = 1,4870,437,437,437
BEGIN DESCRIPTION:
Mapping XS 49c599bc
END DESCRIPTION:
XS GIS Cut Line= 3
      1615493.13      6959913.09      1615928.58      6959411.01
      1616033.48      6958995.14
#Sta/Elev= 30
  4335.4 1545.51  4375.8 1542.94  4410.9 1542.26  4428.6 1539.62  4453.7 1537.74
  4503.1 1538.31  4560.1 1537.17  4579.2 1535.85  4602.8 1533.95  4645.5 1533.64
  4652.2 1534.38  4705.8 1531.07  4715.8 1528.91  4730.0 1528.35  4814.9 1529.13
  4985.5 1529.30  5002.9 1528.69  5013.4 1525.15  5018.6 1525.04  5019.1 1524.54
  5028.9 1525.04  5054.7 1528.36  5084.0 1527.14  5089.2 1528.56  5095.9 1528.04
  5116.6 1529.87  5166.2 1531.29  5290.0 1537.90  5371.5 1540.94  5428.9 1541.96
#Mann=8,-1,0
  4335.4    0.07       0  4428.6   0.035       0  4579.2    0.07       0
  4705.8   0.035       0  4814.9    0.07       0  5018.6    0.07       0
  5028.9    0.07       0  5290.0   0.035       0
Bank Sta=5018.6,5028.9
Exp/Cntr=0.3,0.1

Type RM Length L Ch R = 1,4433,316,316,316
BEGIN DESCRIPTION:
Mapping XS fcbbb5c8
END DESCRIPTION:
XS GIS Cut Line= 3
      1615799.10      6960269.02      1615898.82      6959733.49
      1616273.46      6959191.75
#Sta/Elev= 30
  4454.6 1559.85  4496.3 1556.36  4526.8 1550.99  4557.4 1548.96  4608.2 1542.79
  4760.5 1538.11  4781.1 1539.25  4811.7 1538.37  4839.5 1536.93  4862.5 1532.62
  4872.7 1532.32  4882.9 1535.85  4897.3 1537.29  4923.5 1532.82  4933.7 1532.77
  4943.9 1530.69  4950.1 1526.24  4969.2 1524.63  4969.7 1524.13  4979.7 1524.63
  4984.6 1527.67  5006.8 1528.74  5083.0 1528.78  5113.7 1528.91  5337.9 1529.74
  5373.7 1529.32  5388.6 1526.77  5403.5 1529.14  5425.6 1529.85  5658.0 1535.26
#Mann=7,-1,0
  4454.6    0.07       0  4760.5   0.035       0  4969.2   0.035       0
  4979.7   0.035       0  5083.0    0.07       0  5113.7   0.035       0
  5425.6    0.07       0
Bank Sta=4969.2,4979.7
Exp/Cntr=0.3,0.1

Type RM Length L Ch R = 1,4117,312,312,312
BEGIN DESCRIPTION:
Mapping XS d32f27ea
END DESCRIPTION:
XS GIS Cut Line= 3
      1616183.21      6960112.78      1616193.85      6959786.19
      1616337.08      6959202.16
#Sta/Elev= 30
  4674.1 1539.22  4707.4 1539.53  4808.9 1540.58  4847.8 1540.04  4859.0 1540.29
  4878.3 1536.38  4883.3 1536.18  4889.0 1533.17  4899.0 1531.61  4919.0 1530.73
  4963.7 1524.56  4964.2 1524.06  4974.3 1524.56  4989.0 1524.82  4997.5 1527.33
  5016.3 1527.55  5030.9 1527.86  5050.5 1526.92  5067.3 1527.45  5072.4 1526.91
  5081.4 1527.82  5144.6 1526.95  5204.9 1526.19  5233.6 1528.74  5238.8 1527.08
  5256.4 1528.67  5280.4 1527.95  5358.4 1528.16  5555.0 1533.02  5602.2 1535.07
#Mann=7,-1,0
  4674.1    0.07       0  4707.4   0.035       0  4847.8    0.07       0
  4963.7    0.07       0  4974.3    0.07       0  5016.3   0.035       0
  5144.6    0.07       0
Bank Sta=4963.7,4974.3
Exp/Cntr=0.3,0.1

Type RM Length L Ch R = 1,3805,247,247,247
BEGIN DESCRIPTION:
Mapping XS 266acc0b
END DESCRIPTION:
XS GIS Cut Line= 3
      1616367.73      6959853.20      1616353.84      6959544.88
      1616371.21      6959306.65
#Sta/Elev= 30
  4691.6 1531.14  4712.7 1529.79  4756.9 1528.70  4766.9 1528.24  4816.9 1527.95
  4862.7 1527.05  4867.7 1527.41  4877.0 1526.94  4887.0 1527.12  4894.9 1526.90
  4917.0 1526.85  4937.1 1526.21  4947.1 1526.27  4967.1 1525.77  4977.1 1524.78
  4981.8 1524.58  4982.3 1524.08  4991.9 1524.08  4992.4 1524.58  4996.2 1524.83
  5017.2 1524.68  5027.2 1525.63  5037.2 1527.26  5047.2 1527.59  5057.3 1527.56
  5123.1 1529.58  5151.8 1530.39  5177.6 1531.43  5217.6 1532.22  5239.1 1533.02
#Mann=7,-1,0
  4691.6    0.07       0  4712.7   0.035       0  4894.9    0.07       0
  4981.8    0.07       0  4992.4    0.07       0  5123.1   0.035       0
  5151.8    0.07       0
Bank Sta=4981.8,4992.4
Exp/Cntr=0.3,0.1

Type RM Length L Ch R = 1,3558,161,161,161
BEGIN DESCRIPTION:
Mapping XS 7b2d96c1
END DESCRIPTION:
XS GIS Cut Line= 3
      1616417.71      6959886.58      1616551.06      6959682.38
      1616600.78      6959401.33
#Sta/Elev= 30
  4754.7 1530.59  4780.0 1529.07  4788.5 1529.09  4800.6 1528.86  4810.3 1528.68
  4837.3 1526.65  4896.3 1525.19  4915.5 1525.48  4932.2 1524.78  4940.0 1526.12
  4977.7 1525.54  4982.1 1525.23  4991.3 1522.74  4998.0 1522.65  4998.5 1522.15
  5008.1 1522.15  5008.6 1522.65  5023.3 1522.99  5033.5 1525.72  5049.3 1526.37
  5074.1 1526.44  5094.4 1525.46  5108.5 1527.29  5124.9 1527.39  5135.1 1526.90
  5196.0 1530.82  5206.1 1530.68  5221.7 1531.90  5232.9 1531.74  5284.0 1533.40
#Mann=9,-1,0
  4754.7    0.07       0  4788.5   0.035       0  4800.6    0.07       0
  4915.5   0.035       0  4977.7    0.07       0  4998.0    0.07       0
  5008.6    0.07       0  5124.9   0.035       0  5232.9    0.07       0
Bank Sta=4998,5008.6
Exp/Cntr=0.3,0.1

Type RM Length L Ch R = 1,3397,132,132,132
BEGIN DESCRIPTION:
Mapping XS f6e37aa4
END DESCRIPTION:
XS GIS Cut Line= 3
      1616715.35      6959969.11      1616695.90      6959738.56
      1616706.94      6959441.14
#Sta/Elev= 30
  4768.5 1536.10  4809.8 1534.60  4833.5 1533.42  4839.9 1532.72  4859.9 1531.60
  4870.0 1530.79  4900.1 1525.95  4910.1 1524.98  4930.2 1524.07  4960.3 1524.76
  4980.4 1524.11  4990.4 1524.20  4992.1 1522.08  4992.6 1521.58  5002.6 1521.58
  5003.1 1522.08  5010.4 1523.33  5020.4 1524.28  5030.5 1524.14  5040.5 1524.93
  5070.5 1524.42  5099.3 1525.72  5107.9 1526.21  5112.9 1525.92  5120.5 1526.49
  5160.5 1527.26  5177.0 1528.38  5200.6 1528.76  5220.6 1529.89  5297.5 1532.13
#Mann=5,-1,0
  4768.5   0.035       0  4992.1   0.035       0  5003.1   0.035       0
  5099.3    0.07       0  5177.0   0.035       0
Bank Sta=4992.1,5003.1
Exp/Cntr=0.3,0.1