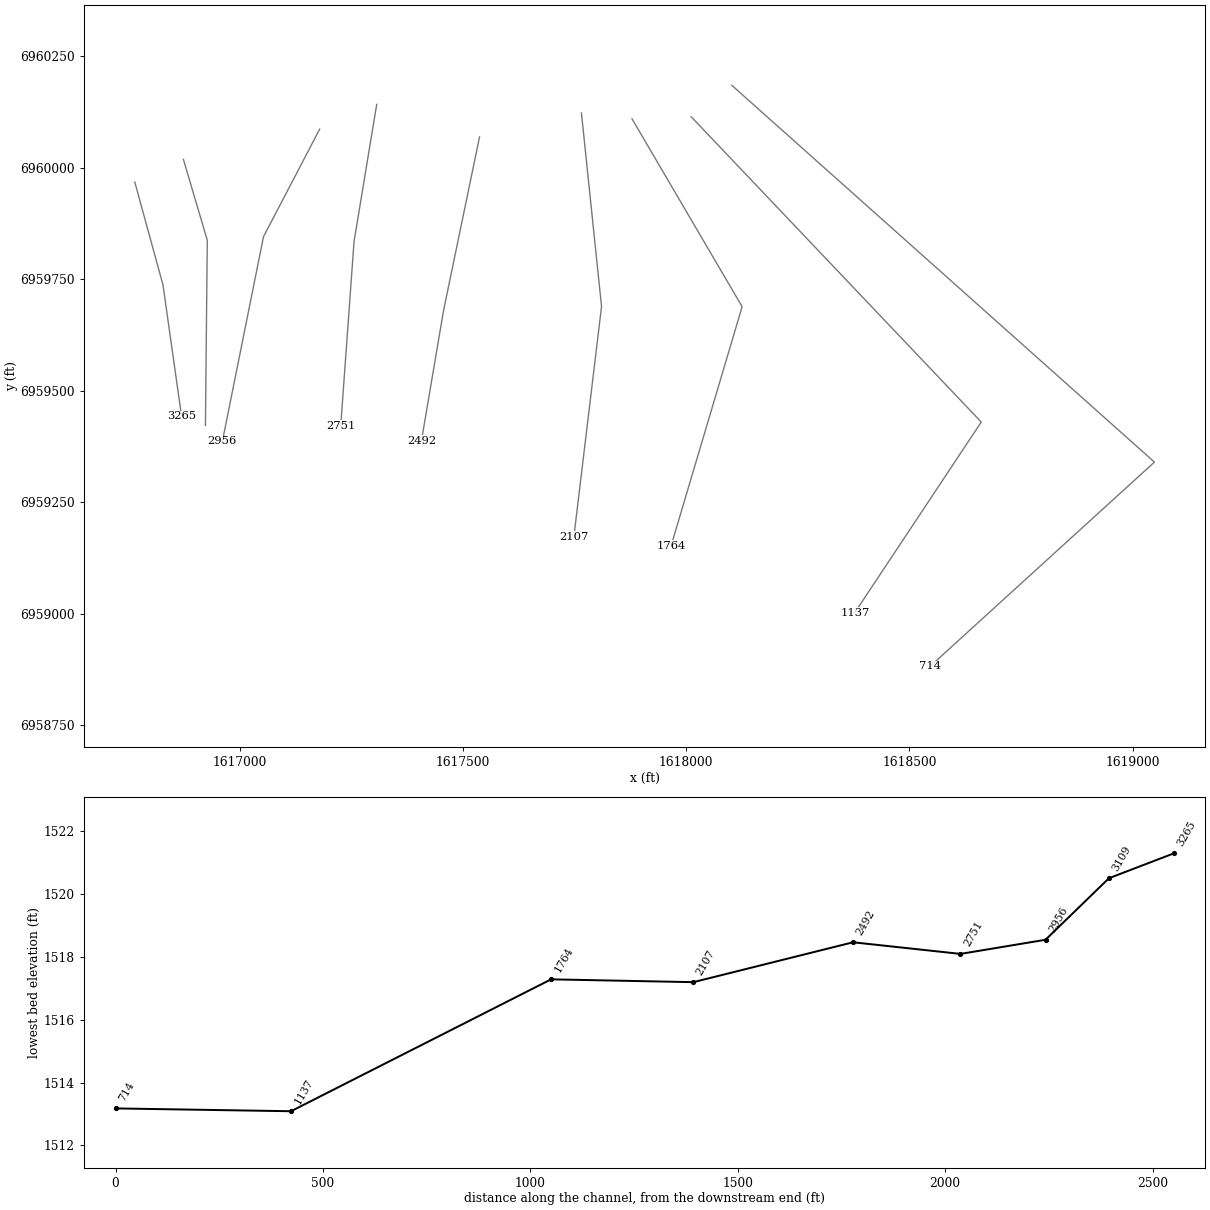
HEC-RAS study Flatrock Creek.prj: Flatrock Creek Base Level Engineering

--- Flatrock Creek.g01 (geometry) --- (continued)

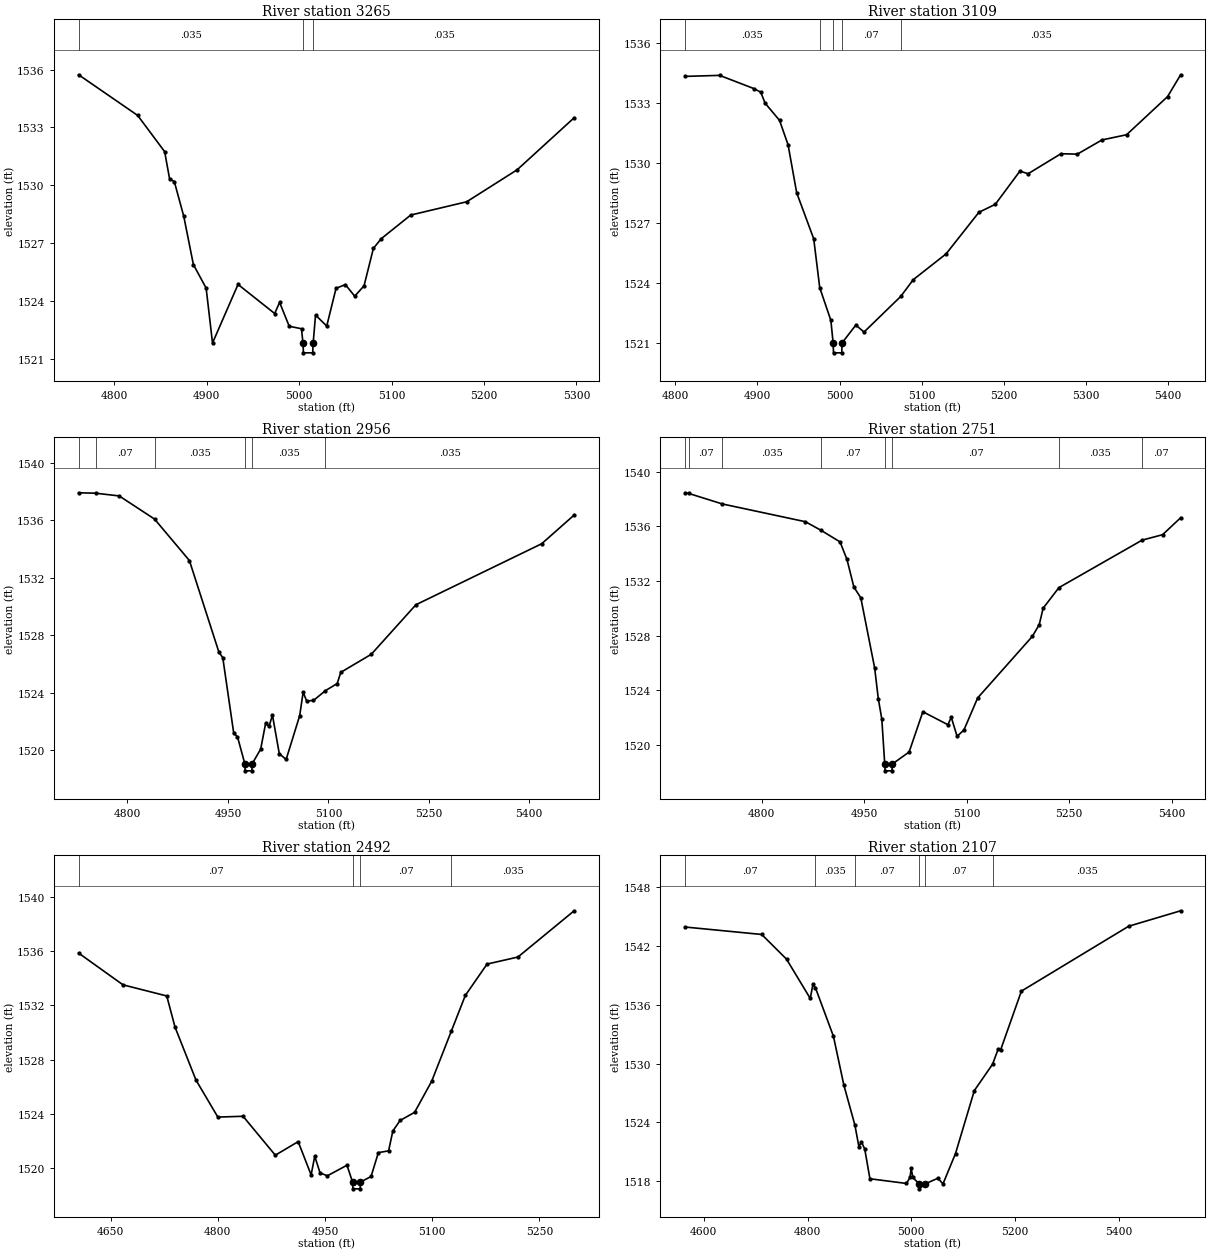
Type RM Length L Ch R = 1,3265,156,156,156
BEGIN DESCRIPTION:
Mapping XS bb956f55
END DESCRIPTION:
XS GIS Cut Line= 3
      1616763.95      6959967.75      1616827.15      6959737.17
      1616868.80      6959442.89
#Sta/Elev= 30
  4761.3 1535.73  4825.2 1533.62  4854.4 1531.74  4859.7 1530.34  4864.9 1530.18
  4875.1 1528.38  4885.5 1525.88  4899.3 1524.66  4906.2 1521.81  4933.8 1524.85
  4973.5 1523.34  4978.8 1523.92  4989.2 1522.68  5002.5 1522.55  5004.1 1521.80
  5004.6 1521.30  5014.6 1521.30  5015.1 1521.80  5017.7 1523.26  5029.8 1522.69
  5039.9 1524.65  5050.0 1524.84  5060.1 1524.24  5070.2 1524.78  5080.3 1526.72
  5088.7 1527.22  5120.7 1528.45  5181.3 1529.14  5235.9 1530.80  5297.6 1533.50
#Mann=3,-1,0
  4761.3   0.035       0  5004.1   0.035       0  5015.1   0.035       0
Bank Sta=5004.1,5015.1
Exp/Cntr=0.3,0.1

Type RM Length L Ch R = 1,3109,153,153,153
BEGIN DESCRIPTION:
Mapping XS e6a0a5cd
END DESCRIPTION:
XS GIS Cut Line= 3
      1616872.99      6960018.40      1616926.46      6959837.17
      1616922.30      6959422.15
#Sta/Elev= 30
  4811.8 1534.34  4853.9 1534.39  4895.6 1533.73  4904.0 1533.55  4909.3 1533.00
  4926.9 1532.14  4937.3 1530.92  4947.8 1528.52  4968.6 1526.21  4975.9 1523.77
  4989.5 1522.13  4992.2 1521.01  4992.7 1520.51  5002.7 1520.51  5003.2 1521.01
  5019.9 1521.90  5029.9 1521.55  5074.6 1523.33  5089.9 1524.17  5129.9 1525.46
  5169.9 1527.54  5189.9 1527.94  5219.9 1529.60  5229.9 1529.47  5269.9 1530.47
  5289.9 1530.45  5319.9 1531.16  5349.9 1531.42  5399.9 1533.33  5415.8 1534.42
#Mann=5,-1,0
  4811.8   0.035       0  4975.9    0.07       0  4992.2    0.07       0
  5003.2    0.07       0  5074.6   0.035       0
Bank Sta=4992.2,5003.2
Exp/Cntr=0.3,0.1

Type RM Length L Ch R = 1,2956,205,205,205
BEGIN DESCRIPTION:
Mapping XS 774788a1
END DESCRIPTION:
XS GIS Cut Line= 3
      1617178.33      6960086.20      1617052.47      6959845.33
      1616960.24      6959386.37
#Sta/Elev= 30
  4727.1 1537.92  4752.8 1537.89  4787.7 1537.70  4840.4 1536.09  4892.5 1533.20
  4936.6 1526.81  4942.3 1526.44  4958.7 1521.17  4964.3 1520.92  4975.2 1519.05
  4975.7 1518.55  4985.8 1518.55  4986.3 1519.05  4998.9 1520.06  5006.3 1521.86
  5011.4 1521.65  5016.5 1522.43  5026.7 1519.75  5036.9 1519.34  5057.2 1522.40
  5062.3 1524.03  5067.5 1523.42  5077.7 1523.45  5095.7 1524.14  5113.2 1524.63
  5118.5 1525.41  5164.1 1526.67  5230.7 1530.12  5418.5 1534.37  5467.0 1536.37
#Mann=6,-1,0
  4727.1   0.035       0  4752.8    0.07       0  4840.4   0.035       0
  4975.2    0.07       0  4986.3   0.035       0  5095.7   0.035       0
Bank Sta=4975.2,4986.3
Exp/Cntr=0.3,0.1

Type RM Length L Ch R = 1,2751,259,259,259
BEGIN DESCRIPTION:
Mapping XS f1596b81
END DESCRIPTION:
XS GIS Cut Line= 3
      1617306.16      6960141.72      1617255.38      6959834.41
      1617225.53      6959421.66
#Sta/Elev= 30
  4687.7 1538.47  4693.1 1538.42  4742.3 1537.65  4863.8 1536.35  4887.0 1535.71
  4914.5 1534.87  4924.6 1533.59  4934.7 1531.57  4944.9 1530.77  4965.1 1525.65
  4970.5 1523.38  4975.6 1521.90  4979.9 1518.60  4980.4 1518.10  4990.5 1518.10
  4991.0 1518.60  5015.6 1519.48  5035.7 1522.43  5072.3 1521.48  5077.3 1522.02
  5085.8 1520.63  5095.8 1521.09  5115.9 1523.44  5196.1 1527.96  5206.1 1528.82
  5211.7 1530.01  5234.8 1531.52  5356.6 1535.00  5386.6 1535.40  5413.0 1536.64
#Mann=8,-1,0
  4687.7   0.035       0  4693.1    0.07       0  4742.3   0.035       0
  4887.0    0.07       0  4979.9    0.07       0  4991.0    0.07       0
  5234.8   0.035       0  5356.6    0.07       0
Bank Sta=4979.9,4991
Exp/Cntr=0.3,0.1

Type RM Length L Ch R = 1,2492,385,385,385
BEGIN DESCRIPTION:
Mapping XS 757391cd
END DESCRIPTION:
XS GIS Cut Line= 3
      1617536.63      6960068.78      1617455.90      6959679.46
      1617406.43      6959387.83
#Sta/Elev= 30
  4605.2 1535.85  4667.3 1533.51  4728.5 1532.69  4740.1 1530.39  4769.4 1526.49
  4800.0 1523.76  4835.3 1523.82  4880.4 1520.95  4912.4 1521.95  4930.5 1519.50
  4935.6 1520.87  4943.0 1519.65  4953.2 1519.43  4980.7 1520.21  4988.5 1518.97
  4989.0 1518.47  4999.1 1518.47  4999.6 1518.97  5014.4 1519.38  5024.6 1521.14
  5038.9 1521.27  5044.9 1522.74  5055.0 1523.51  5075.3 1524.11  5099.2 1526.40
  5126.8 1530.11  5146.3 1532.73  5176.7 1535.04  5219.9 1535.56  5298.6 1538.97
#Mann=4,-1,0
  4605.2    0.07       0  4988.5    0.07       0  4999.6    0.07       0
  5126.8   0.035       0
Bank Sta=4988.5,4999.6
Exp/Cntr=0.3,0.1

Type RM Length L Ch R = 1,2107,343,343,343
BEGIN DESCRIPTION:
Mapping XS 9b44debb
END DESCRIPTION:
XS GIS Cut Line= 3
      1617765.01      6960122.44      1617810.05      6959688.77
      1617748.07      6959173.18
#Sta/Elev= 30
  4564.0 1543.95  4711.7 1543.19  4759.5 1540.67  4805.3 1536.65  4810.4 1538.09
  4815.3 1537.74  4850.0 1532.78  4870.1 1527.79  4891.4 1523.70  4899.0 1521.51
  4904.0 1521.98  4910.3 1521.27  4920.3 1518.23  4990.7 1517.75  4997.6 1518.36
  4999.8 1519.28  5003.1 1518.36  5015.3 1517.70  5015.8 1517.20  5026.5 1517.70
  5051.1 1518.28  5061.2 1517.71  5085.3 1520.81  5121.6 1527.24  5156.8 1529.94
  5167.5 1531.47  5172.5 1531.43  5212.3 1537.40  5419.1 1544.03  5519.3 1545.61
#Mann=6,-1,0
  4564.0    0.07       0  4815.3   0.035       0  4891.4    0.07       0
  5015.3    0.07       0  5026.5    0.07       0  5156.8   0.035       0
Bank Sta=5015.3,5026.5
Exp/Cntr=0.3,0.1

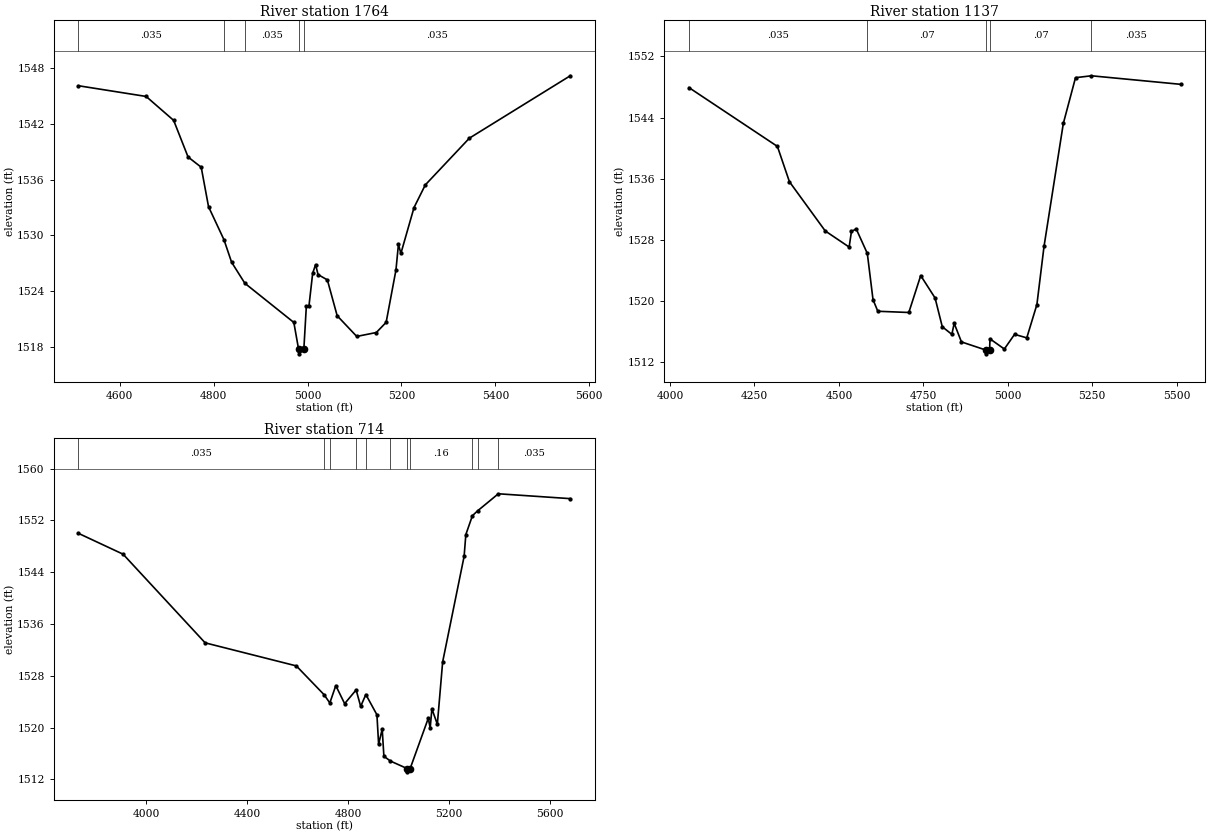
Type RM Length L Ch R = 1,1764,627,627,627
BEGIN DESCRIPTION:
Mapping XS 7c07fca7
END DESCRIPTION:
XS GIS Cut Line= 3
      1617878.28      6960109.43      1618125.15      6959688.36
      1617965.80      6959152.03
#Sta/Elev= 30
  4511.9 1546.08  4656.1 1544.93  4714.7 1542.36  4745.4 1538.43  4773.4 1537.33
  4789.0 1533.09  4821.9 1529.54  4838.1 1527.13  4866.3 1524.87  4970.7 1520.66
  4980.8 1517.79  4981.3 1517.29  4992.0 1517.79  4997.3 1522.38  5002.8 1522.38
  5010.8 1525.94  5017.0 1526.87  5022.3 1525.80  5042.1 1525.23  5063.0 1521.38
  5104.7 1519.16  5146.4 1519.58  5167.3 1520.67  5188.2 1526.29  5193.5 1529.05
  5198.7 1528.07  5226.7 1533.00  5250.7 1535.43  5344.6 1540.45  5559.5 1547.15
#Mann=5,-1,0
  4511.9   0.035       0  4821.9    0.07       0  4866.3   0.035       0
  4980.8   0.035       0  4992.0   0.035       0
Bank Sta=4980.8,4992
Exp/Cntr=0.3,0.1

Type RM Length L Ch R = 1,1137,423,423,423
BEGIN DESCRIPTION:
Mapping XS 05693757
END DESCRIPTION:
XS GIS Cut Line= 3
      1618010.94      6960114.02      1618661.04      6959429.82
      1618377.78      6959002.96
#Sta/Elev= 30
  4056.2 1547.92  4317.9 1540.23  4353.5 1535.61  4459.5 1529.17  4530.3 1527.06
  4537.2 1529.11  4551.3 1529.43  4584.1 1526.23  4601.0 1520.18  4615.2 1518.66
  4707.0 1518.50  4742.2 1523.33  4784.7 1520.40  4806.1 1516.63  4834.4 1515.64
  4841.3 1517.08  4862.8 1514.65  4934.8 1513.59  4935.3 1513.09  4946.1 1513.59
  4947.3 1515.05  4989.8 1513.72  5020.1 1515.64  5056.2 1515.18  5086.2 1519.54
  5107.3 1527.15  5164.4 1543.23  5200.5 1549.22  5247.4 1549.47  5512.3 1548.35
#Mann=5,-1,0
  4056.2   0.035       0  4584.1    0.07       0  4934.8    0.07       0
  4946.1    0.07       0  5247.4   0.035       0
Bank Sta=4934.8,4946.1
Exp/Cntr=0.3,0.1

Type RM Length L Ch R = 1,714,0,0,0
BEGIN DESCRIPTION:
Mapping XS 2af0cfab
END DESCRIPTION:
XS GIS Cut Line= 3
      1618102.08      6960184.40      1619049.15      6959340.06
      1618546.32      6958882.27
#Sta/Elev= 30
  3731.2 1550.01  3908.1 1546.79  4233.3 1533.10  4594.5 1529.54  4704.1 1525.11
  4727.3 1523.82  4750.9 1526.50  4786.0 1523.71  4831.5 1525.83  4849.5 1523.29
  4870.0 1525.12  4913.9 1521.99  4920.6 1517.44  4934.8 1519.78  4941.5 1515.59
  4967.6 1514.84  5034.2 1513.68  5034.7 1513.18  5045.5 1513.68  5117.5 1521.46
  5124.9 1519.93  5131.7 1522.91  5153.3 1520.53  5174.3 1530.15  5259.4 1546.46
  5266.2 1549.82  5292.3 1552.74  5313.0 1553.49  5395.0 1556.12  5680.0 1555.37
#Mann=11,-1,0
  3731.2   0.035       0  4704.1    0.07       0  4727.3   0.035       0
  4831.5    0.16       0  4870.0   0.035       0  4967.6    0.16       0
  5034.2    0.07       0  5045.5    0.16       0  5292.3   0.035       0
  5313.0    0.07       0  5395.0   0.035       0
Bank Sta=5034.2,5045.5
Exp/Cntr=0.3,0.1

Chan Stop Cuts=-1