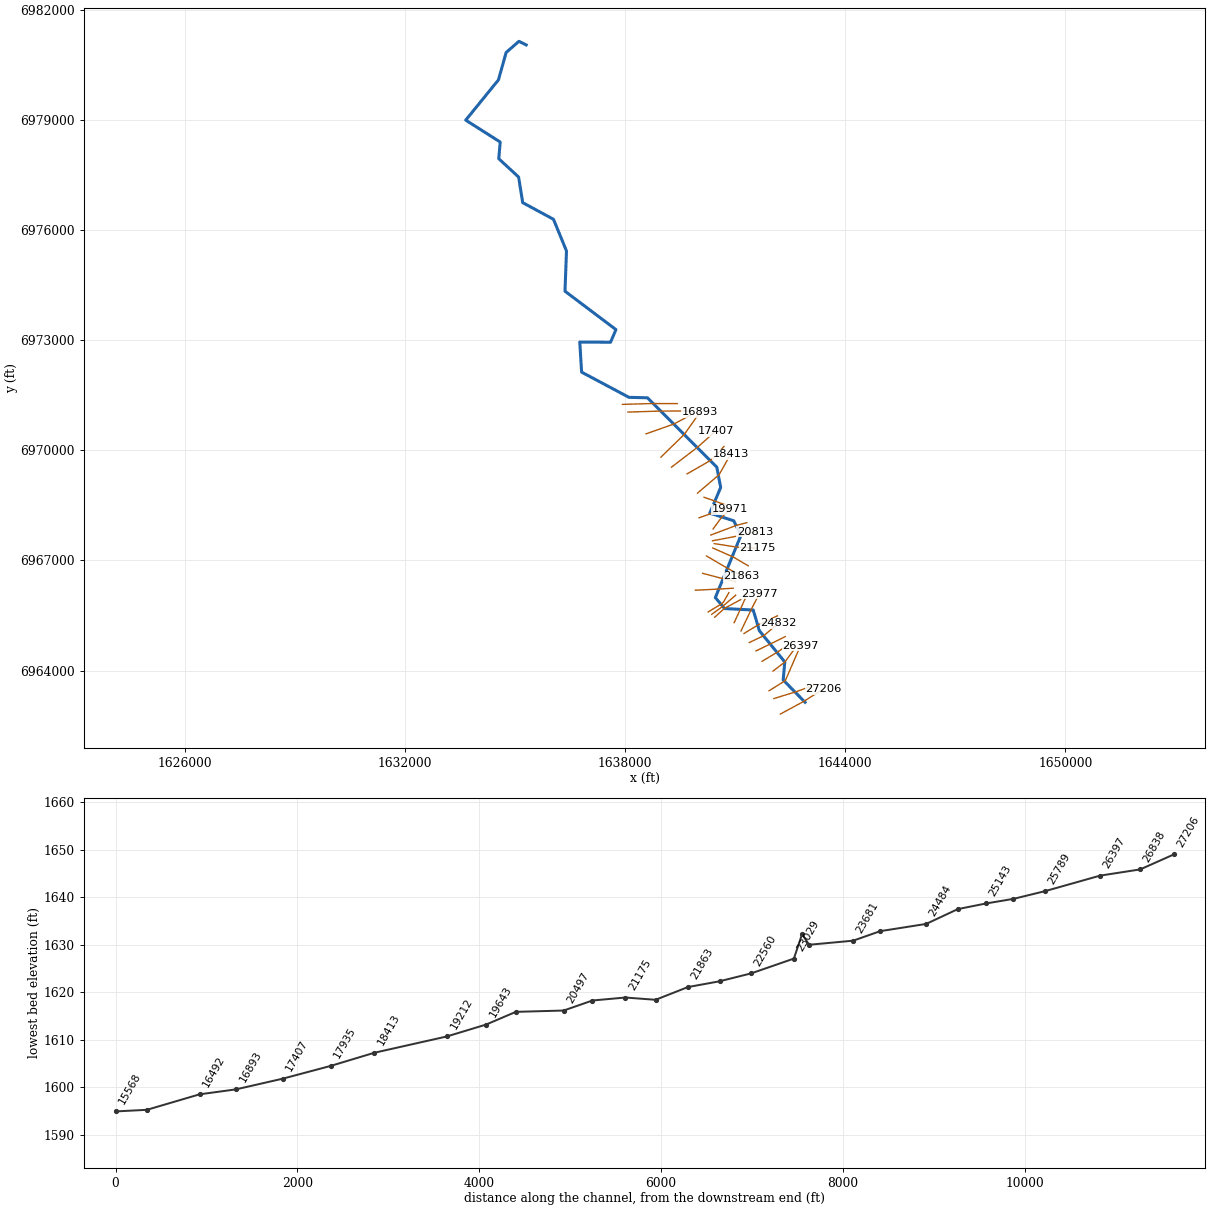
--- Hog Creek.prj (project) ---

Proj Title=Hog Creek Base Level Engineering
Current Plan=p01
Default Exp/Contr=0.3,0.1
English Units
Geom File=g01
Flow File=f01
Plan File=p01
BEGIN DESCRIPTION:
Hog Creek
END DESCRIPTION:

--- Hog Creek.p01 (plan) ---

Plan Title=Multiple Run
Short Identifier=Multiple
Geom File=g01
Flow File=f01
Subcritical Flow
K Sum by GR= 0
Std Step Tol= 0.01
Critical Tol= 0.01
Num of Std Step Trials= 20
Max Error Tol= 0.3
Flow Tol Ratio= 0.001
Split Flow NTrial= 30
Split Flow Tol= 0.02
Split Flow Ratio= 0.02
Log Output Level= 0
Friction Slope Method= 1
Unsteady Friction Slope Method= 2
Unsteady Bridges Friction Slope Method= 1
Parabolic Critical Depth
Global Vel Dist=  1 , 1 , 1
Global Log Level= 0
CheckData=True
Encroach Param= -1, 0, 0, 0
BEGIN DESCRIPTION:
Multiple Run
END DESCRIPTION:

--- Hog Creek.f01 (steady flow) ---

Flow Title=Multiple
Number of Profiles=7
Profile Names=10-year,25-year,50-year,1pct_min,100-year,1pct_plu,500-year
River Rch & RM= Hog Creek,Reach-1,27206
     204     278     337     203     406     810     597
River Rch & RM= Hog Creek,Reach-1,25789
     321     446     550     337     673    1343    1020
River Rch & RM= Hog Creek,Reach-1,18413
     499     708     886     550    1097    2189    1707
River Rch & RM= Hog Creek,Reach-1,12962
     579     827    1038     647    1290    2574    2019
River Rch & RM= Hog Creek,Reach-1,8480
     664     955    1205     754    1504    3002    2378
River Rch & RM= Hog Creek,Reach-1,3442
     767    1115    1415     892    1779    3550    2851
Boundary for River Rch & Prof#=Hog Creek,Reach-1,1
Up Type=0
Dn Type=3
Dn Slope=0.005
Boundary for River Rch & Prof#=Hog Creek,Reach-1,2
Up Type=0
Dn Type=3
Dn Slope=0.005
Boundary for River Rch & Prof#=Hog Creek,Reach-1,3
Up Type=0
Dn Type=3
Dn Slope=0.005
Boundary for River Rch & Prof#=Hog Creek,Reach-1,4
Up Type=0
Dn Type=3
Dn Slope=0.005
Boundary for River Rch & Prof#=Hog Creek,Reach-1,5
Up Type=0
Dn Type=3
Dn Slope=0.005
Boundary for River Rch & Prof#=Hog Creek,Reach-1,6
Up Type=0
Dn Type=3
Dn Slope=0.005
Boundary for River Rch & Prof#=Hog Creek,Reach-1,7
Up Type=0
Dn Type=3
Dn Slope=0.005

--- Hog Creek.g01 (geometry) ---

Geom Title=Existing Conditions

River Reach=Hog Creek,Reach-1
Reach XY= 30
      1642905.00      6963138.00      1642308.16      6963746.34
      1642351.47      6964236.53      1641660.52      6965085.57
      1641491.39      6965651.24      1640710.90      6965690.23
      1640458.75      6965989.55      1641155.78      6967678.86
      1640961.47      6968080.30      1640308.52      6968289.28
      1640605.00      6968988.00      1640499.17      6969540.30
      1638611.07      6971429.85      1638106.56      6971441.74
      1636815.76      6972128.32      1636765.76      6972947.68
      1637603.53      6972941.53      1637751.47      6973286.54
      1636362.81      6974331.81      1636403.78      6975427.50
      1636049.18      6976290.31      1635210.18      6976743.44
      1635099.17      6977440.30      1634558.74      6977939.56
      1634597.19      6978394.19      1633658.52      6978989.46
      1634549.17      6980085.70      1634760.18      6980832.56
      1635106.65      6981134.89      1635305.00      6981038.00

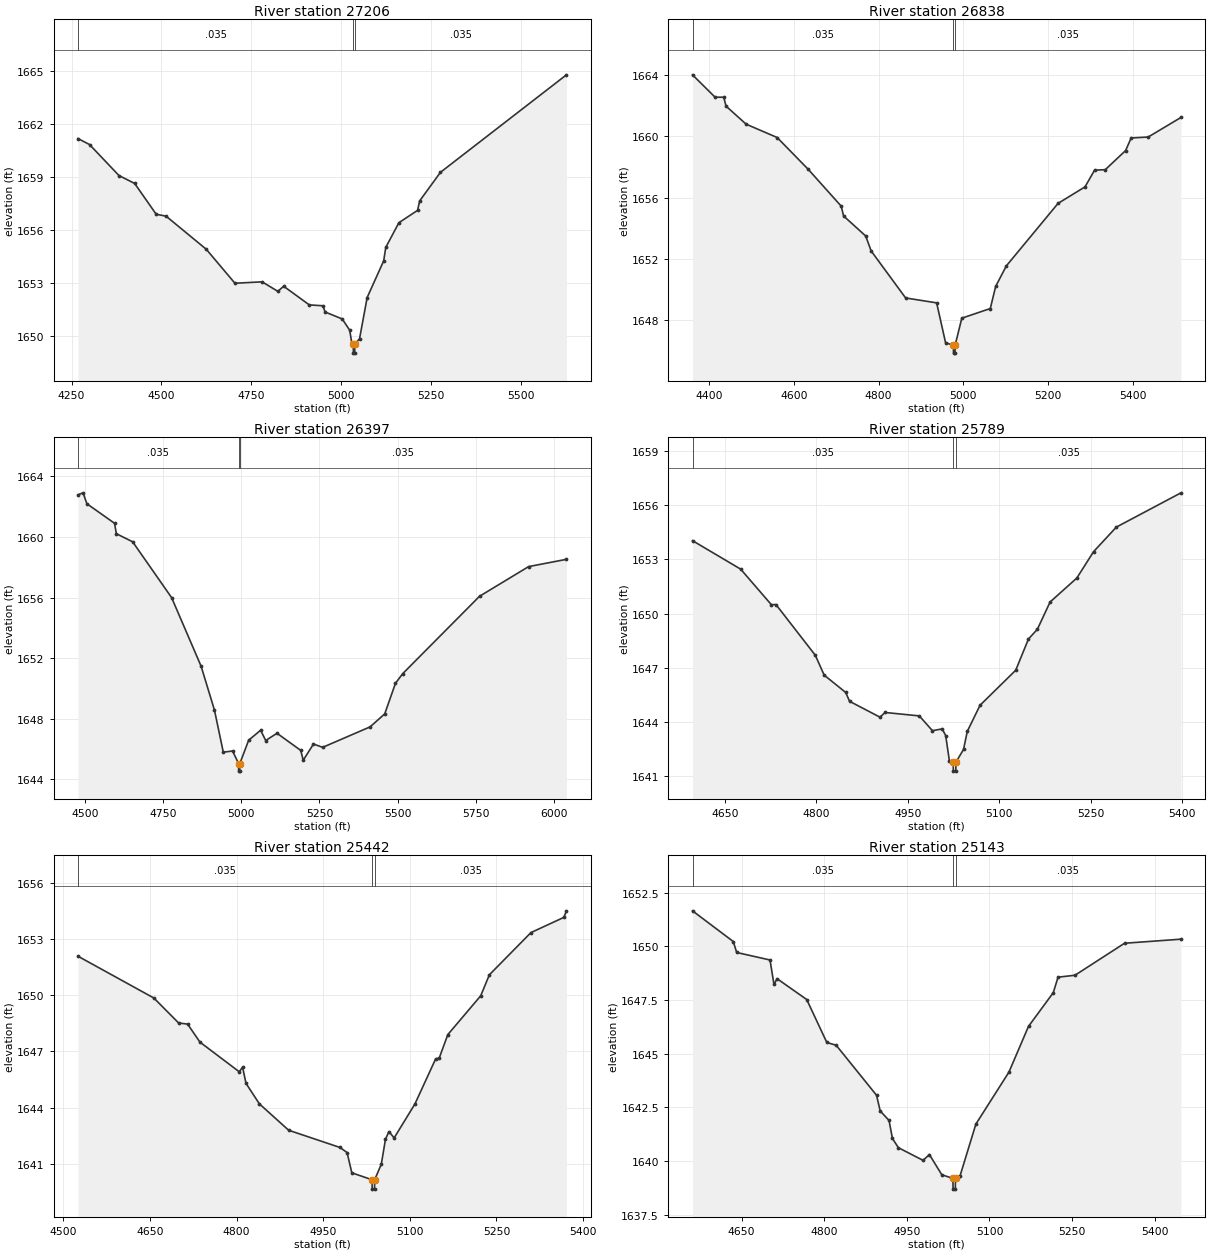
Type RM Length L Ch R = 1,27206,368,368,368
BEGIN DESCRIPTION:
Hog Creek 59.0
END DESCRIPTION:
XS GIS Cut Line= 3
      1642231.12      6962817.98      1642874.90      6963166.99
      1643405.62      6963500.28
#Sta/Elev= 30
  4267.7 1661.19  4299.9 1660.85  4381.7 1659.09  4425.4 1658.64  4485.3 1656.89
  4512.9 1656.78  4624.7 1654.90  4704.4 1652.97  4780.1 1653.05  4823.8 1652.51
  4840.0 1652.80  4911.3 1651.74  4949.3 1651.69  4955.0 1651.34  5003.0 1650.94
  5023.7 1650.30  5029.9 1649.52  5033.8 1649.50  5034.0 1649.00  5037.5 1649.00
  5037.8 1649.50  5051.1 1649.82  5072.3 1652.16  5118.2 1654.24  5124.1 1655.01
  5160.6 1656.41  5212.5 1657.11  5218.4 1657.65  5276.1 1659.27  5626.7 1664.81
#Mann=3,-1,0
  4267.7   0.035       0  5033.8   0.035       0  5037.8   0.035       0
Bank Sta=5033.8,5037.8
Exp/Cntr=0.3,0.1

Type RM Length L Ch R = 1,26838,441,441,441
BEGIN DESCRIPTION:
Mapping XS 32285b24
END DESCRIPTION:
XS GIS Cut Line= 3
      1642054.04      6963239.86      1642663.42      6963427.36
      1643147.80      6963604.44
#Sta/Elev= 30
  4360.6 1664.02  4413.9 1662.56  4434.4 1662.56  4439.7 1661.98  4487.2 1660.80
  4560.4 1659.93  4633.6 1657.86  4711.7 1655.45  4717.3 1654.81  4769.6 1653.50
  4782.3 1652.53  4863.8 1649.46  4937.0 1649.14  4958.0 1646.55  4976.5 1646.36
  4976.8 1645.86  4980.3 1645.86  4980.5 1646.36  4996.4 1648.14  5063.7 1648.77
  5076.3 1650.21  5101.5 1651.55  5223.6 1655.63  5287.3 1656.71  5309.9 1657.80
  5335.1 1657.83  5383.2 1659.08  5396.2 1659.90  5436.4 1659.96  5513.9 1661.24
#Mann=3,-1,0
  4360.6   0.035       0  4976.5   0.035       0  4980.5   0.035       0
Bank Sta=4976.5,4980.5
Exp/Cntr=0.3,0.1

Type RM Length L Ch R = 1,26397,608,608,608
BEGIN DESCRIPTION:
Mapping XS 8cb2ab7c
END DESCRIPTION:
XS GIS Cut Line= 3
      1641921.21      6963450.78      1642366.54      6963729.44
      1642780.32      6964679.30
#Sta/Elev= 30
  4478.1 1662.79  4494.4 1662.92  4506.6 1662.20  4595.0 1660.91  4600.9 1660.22
  4652.8 1659.69  4777.5 1656.00  4871.8 1651.47  4914.5 1648.57  4942.6 1645.80
  4972.3 1645.88  4991.5 1645.05  4991.7 1644.55  4995.2 1644.55  4995.5 1645.05
  5023.7 1646.59  5062.0 1647.25  5078.2 1646.57  5114.3 1647.05  5190.1 1645.92
  5198.2 1645.27  5230.9 1646.34  5260.3 1646.12  5411.8 1647.47  5458.7 1648.33
  5493.0 1650.35  5516.4 1650.99  5761.6 1656.09  5918.5 1658.05  6039.5 1658.53
#Mann=3,-1,0
  4478.1   0.035       0  4991.5   0.035       0  4995.5   0.035       0
Bank Sta=4991.5,4995.5
Exp/Cntr=0.3,0.1

Type RM Length L Ch R = 1,25789,347,347,347
BEGIN DESCRIPTION:
Mapping XS 6736e86c
END DESCRIPTION:
XS GIS Cut Line= 3
      1642032.16      6963989.31      1642353.31      6964234.07
      1642589.23      6964553.26
#Sta/Elev= 30
  4597.2 1654.04  4676.2 1652.46  4726.5 1650.49  4734.0 1650.50  4798.5 1647.69
  4813.0 1646.59  4848.3 1645.63  4854.6 1645.14  4904.5 1644.26  4912.8 1644.52
  4969.0 1644.33  4990.5 1643.51  5006.5 1643.61  5012.2 1643.24  5018.4 1641.81
  5024.5 1641.77  5024.8 1641.27  5028.7 1641.27  5029.1 1641.77  5041.4 1642.47
  5047.6 1643.47  5068.5 1644.92  5127.0 1646.86  5147.9 1648.59  5162.5 1649.13
  5183.3 1650.64  5227.2 1651.97  5254.6 1653.43  5291.9 1654.79  5397.9 1656.69
#Mann=3,-1,0
  4597.2   0.035       0  5024.5   0.035       0  5029.1   0.035       0
Bank Sta=5024.5,5029.1
Exp/Cntr=0.3,0.1

Type RM Length L Ch R = 1,25442,299,299,299
BEGIN DESCRIPTION:
Mapping XS 64c5e959
END DESCRIPTION:
XS GIS Cut Line= 3
      1641735.25      6964256.64      1642144.97      6964501.43
      1642451.13      6964707.27
#Sta/Elev= 30
  4525.1 1652.07  4656.6 1649.84  4699.5 1648.51  4715.0 1648.45  4736.4 1647.49
  4804.4 1645.91  4810.3 1646.15  4816.2 1645.29  4839.3 1644.20  4890.1 1642.79
  4979.1 1641.87  4991.3 1641.60  4999.5 1640.52  5034.5 1640.15  5034.8 1639.65
  5038.8 1639.65  5039.1 1640.15  5050.6 1640.98  5057.8 1642.31  5063.8 1642.72
  5072.8 1642.38  5108.8 1644.19  5144.8 1646.60  5150.8 1646.63  5165.8 1647.89
  5222.8 1649.96  5237.8 1651.08  5309.8 1653.33  5366.8 1654.14  5371.3 1654.49
#Mann=3,-1,0
  4525.1   0.035       0  5034.5   0.035       0  5039.1   0.035       0
Bank Sta=5034.5,5039.1
Exp/Cntr=0.3,0.1

Type RM Length L Ch R = 1,25143,311,311,311
BEGIN DESCRIPTION:
Mapping XS b5c47f32
END DESCRIPTION:
XS GIS Cut Line= 3
      1641568.43      6964537.72      1641962.51      6964728.69
      1642365.29      6964926.61
#Sta/Elev= 30
  4560.9 1651.65  4634.9 1650.22  4641.1 1649.71  4701.6 1649.36  4708.8 1648.22
  4714.4 1648.49  4768.2 1647.52  4804.7 1645.52  4821.7 1645.39  4895.0 1643.06
  4901.6 1642.33  4917.6 1641.89  4923.8 1641.05  4934.6 1640.62  4979.4 1640.03
  4990.9 1640.30  5013.4 1639.36  5033.6 1639.19  5033.9 1638.69  5037.9 1638.69
  5038.3 1639.19  5046.2 1639.28  5075.3 1641.72  5135.3 1644.14  5170.8 1646.27
  5215.8 1647.84  5224.4 1648.56  5255.2 1648.65  5345.1 1650.14  5447.6 1650.33
#Mann=3,-1,0
  4560.9   0.035       0  5033.6   0.035       0  5038.3   0.035       0
Bank Sta=5033.6,5038.3
Exp/Cntr=0.3,0.1

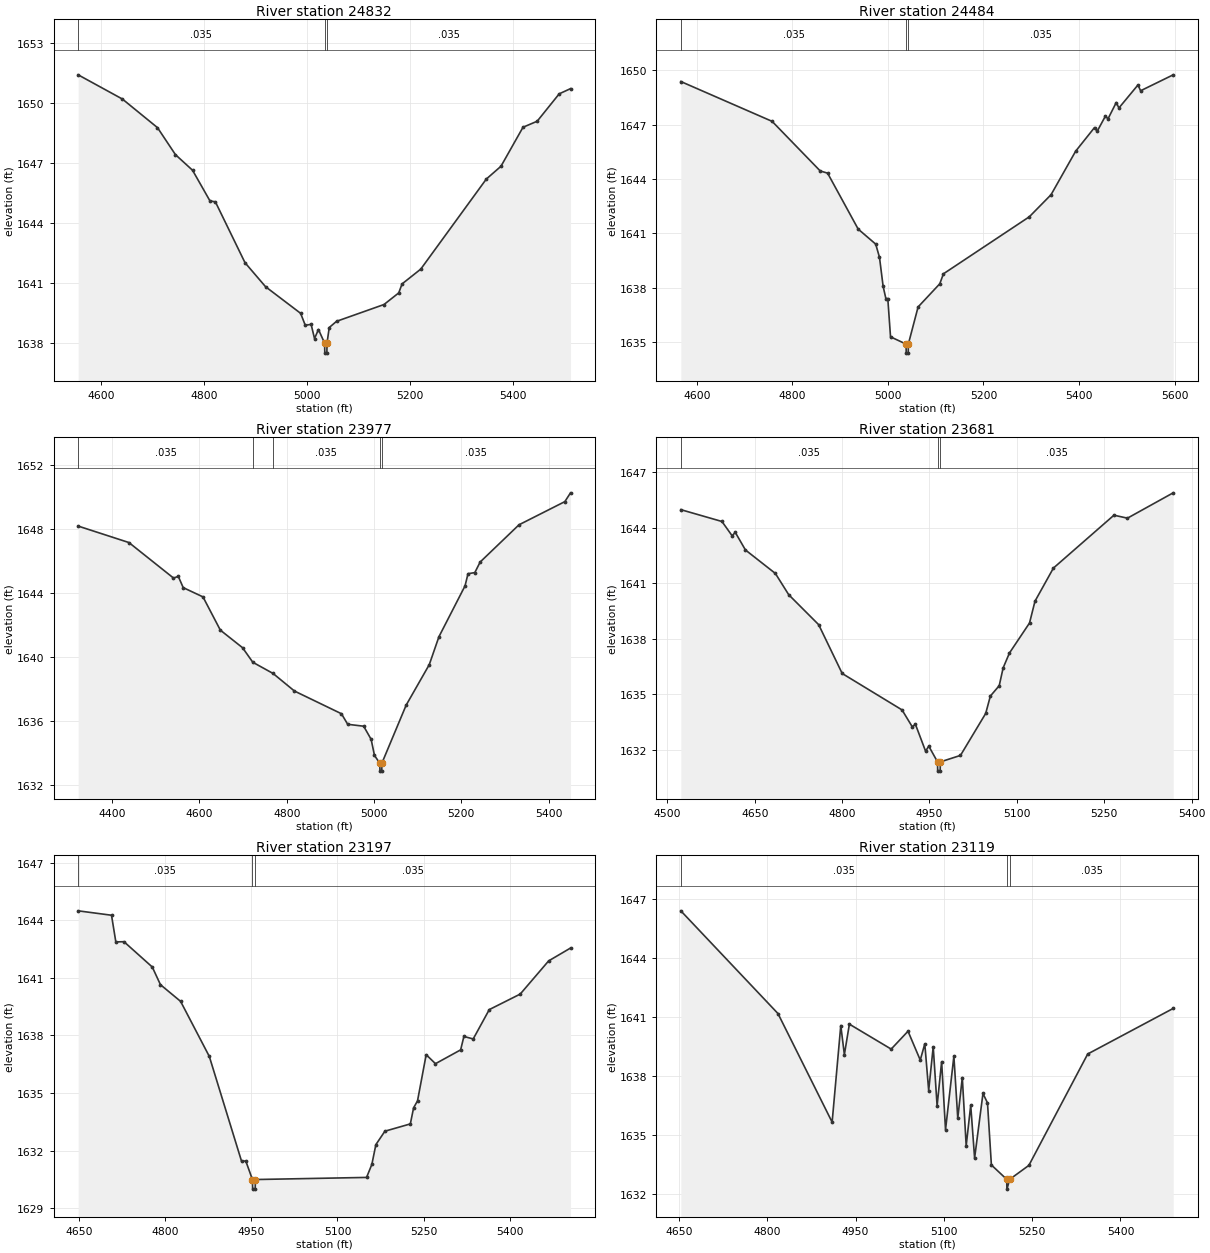
Type RM Length L Ch R = 1,24832,348,348,348
BEGIN DESCRIPTION:
Mapping XS 17781de5
END DESCRIPTION:
XS GIS Cut Line= 3
      1641384.34      6964765.13      1641785.42      6964956.12
      1642174.29      6965289.43
#Sta/Elev= 30
  4554.7 1651.41  4640.6 1650.20  4708.8 1648.77  4743.7 1647.42  4776.9 1646.64
  4810.7 1645.11  4821.3 1645.06  4878.8 1642.02  4918.7 1640.82  4986.8 1639.49
  4995.9 1638.89  5007.2 1638.94  5013.8 1638.23  5021.5 1638.68  5033.4 1638.00
  5033.8 1637.50  5037.8 1637.50  5038.1 1638.00  5042.4 1638.78  5056.6 1639.09
  5148.8 1639.93  5177.4 1640.51  5183.9 1640.96  5220.2 1641.70  5347.5 1646.20
  5376.0 1646.84  5418.8 1648.79  5446.3 1649.09  5489.1 1650.46  5511.1 1650.72
#Mann=3,-1,0
  4554.7   0.035       0  5033.4   0.035       0  5038.1   0.035       0
Bank Sta=5033.4,5038.1
Exp/Cntr=0.3,0.1

Type RM Length L Ch R = 1,24484,507,507,507
BEGIN DESCRIPTION:
Mapping XS 49ffcf39
END DESCRIPTION:
XS GIS Cut Line= 3
      1641240.04      6965011.55      1641609.85      6965237.25
      1642149.47      6965493.23
#Sta/Elev= 30
  4566.6 1649.38  4757.7 1647.18  4858.4 1644.44  4873.8 1644.32  4937.8 1641.23
  4974.5 1640.40  4982.4 1639.67  4990.0 1638.07  4995.8 1637.39  4999.8 1637.39
  5005.5 1635.28  5038.0 1634.88  5038.4 1634.38  5042.5 1634.38  5042.8 1634.88
  5063.2 1636.93  5108.6 1638.21  5116.2 1638.76  5296.0 1641.91  5341.5 1643.13
  5392.9 1645.53  5432.5 1646.84  5438.0 1646.63  5455.2 1647.47  5460.7 1647.32
  5477.9 1648.22  5483.5 1647.92  5523.4 1649.19  5528.9 1648.87  5597.1 1649.75
#Mann=3,-1,0
  4566.6   0.035       0  5038.0   0.035       0  5042.8   0.035       0
Bank Sta=5038,5042.8
Exp/Cntr=0.3,0.1

Type RM Length L Ch R = 1,23977,296,296,296
BEGIN DESCRIPTION:
Mapping XS 1f4d20fb
END DESCRIPTION:
XS GIS Cut Line= 3
      1641158.45      6965080.98      1641451.86      6965693.85
      1641656.68      6966093.09
#Sta/Elev= 30
  4322.0 1648.18  4438.3 1647.15  4540.4 1644.93  4551.5 1645.03  4562.7 1644.33
  4608.0 1643.75  4647.8 1641.67  4698.7 1640.57  4722.2 1639.66  4768.6 1638.96
  4817.6 1637.86  4925.3 1636.44  4939.6 1635.78  4976.2 1635.66  4993.3 1634.84
  5001.0 1633.83  5013.1 1633.35  5013.5 1632.85  5017.6 1632.85  5018.0 1633.35
  5073.6 1636.98  5126.5 1639.51  5148.7 1641.26  5208.5 1644.44  5215.3 1645.20
  5230.9 1645.27  5243.1 1645.93  5332.1 1648.26  5437.2 1649.71  5450.2 1650.26
#Mann=5,-1,0
  4322.0   0.035       0  4722.2    0.07       0  4768.6   0.035       0
  5013.1   0.035       0  5018.0   0.035       0
Bank Sta=5013.1,5018
Exp/Cntr=0.3,0.1

Type RM Length L Ch R = 1,23681,484,484,484
BEGIN DESCRIPTION:
Mapping XS fce5e685
END DESCRIPTION:
XS GIS Cut Line= 3
      1640972.01      6965305.45      1641173.39      6965741.19
      1641321.98      6966074.66
#Sta/Elev= 30
  4523.2 1644.99  4593.8 1644.35  4611.2 1643.58  4616.7 1643.76  4634.1 1642.81
  4685.5 1641.54  4708.4 1640.39  4759.8 1638.77  4800.2 1636.13  4902.9 1634.16
  4920.4 1633.25  4925.9 1633.38  4943.3 1631.93  4948.8 1632.20  4963.8 1631.35
  4964.1 1630.85  4968.3 1630.85  4968.7 1631.35  5003.2 1631.70  5046.5 1633.97
  5054.5 1634.91  5069.7 1635.47  5076.4 1636.43  5087.3 1637.24  5121.7 1638.86
  5131.1 1640.04  5162.7 1641.83  5266.6 1644.69  5289.8 1644.53  5368.3 1645.90
#Mann=3,-1,0
  4523.2   0.035       0  4963.8   0.035       0  4968.7   0.035       0
Bank Sta=4963.8,4968.7
Exp/Cntr=0.3,0.1

Type RM Length L Ch R = 1,23197,78,78,78
BEGIN DESCRIPTION:
Mapping XS bd671af5
END DESCRIPTION:
XS GIS Cut Line= 3
      1640444.20      6965456.45      1640706.37      6965694.31
      1641149.58      6965933.23
#Sta/Elev= 30
  4648.4 1644.50  4706.5 1644.27  4714.0 1642.88  4728.2 1642.89  4777.5 1641.57
  4791.7 1640.65  4826.8 1639.78  4876.8 1636.91  4933.0 1631.44  4940.3 1631.46
  4951.9 1630.49  4952.3 1629.99  4956.7 1629.99  4957.1 1630.49  5150.7 1630.60
  5159.9 1631.28  5166.9 1632.31  5182.6 1633.01  5226.9 1633.39  5232.6 1634.23
  5239.4 1634.59  5254.5 1637.00  5270.7 1636.53  5314.5 1637.25  5320.2 1637.95
  5336.4 1637.82  5364.4 1639.35  5418.3 1640.16  5467.8 1641.89  5505.9 1642.56
#Mann=3,-1,0
  4648.4   0.035       0  4951.9   0.035       0  4957.1   0.035       0
Bank Sta=4951.9,4957.1
Exp/Cntr=0.3,0.1

Type RM Length L Ch R = 1,23119,90,90,90
BEGIN DESCRIPTION:
Mapping XS 432b216e
END DESCRIPTION:
XS GIS Cut Line= 3
      1640360.93      6965532.88      1640645.61      6965739.45
      1641014.01      6966054.24
#Sta/Elev= 30
  4653.3 1646.40  4818.3 1641.17  4910.3 1635.64  4925.0 1640.56  4931.1 1639.08
  4939.6 1640.63  5010.6 1639.36  5039.2 1640.27  5060.0 1638.80  5067.7 1639.63
  5074.3 1637.25  5082.0 1639.48  5088.6 1636.47  5096.3 1638.72  5102.9 1635.25
  5117.1 1639.00  5123.7 1635.84  5131.4 1637.91  5138.0 1634.44  5145.7 1636.50
  5152.3 1633.81  5166.5 1637.10  5174.2 1636.62  5180.8 1633.46  5206.8 1632.73
  5207.2 1632.23  5212.0 1632.73  5244.5 1633.44  5344.4 1639.11  5489.6 1641.43
#Mann=3,-1,0
  4653.3   0.035       0  5206.8   0.035       0  5212.0   0.035       0
Bank Sta=5206.8,5212
Exp/Cntr=0.3,0.1

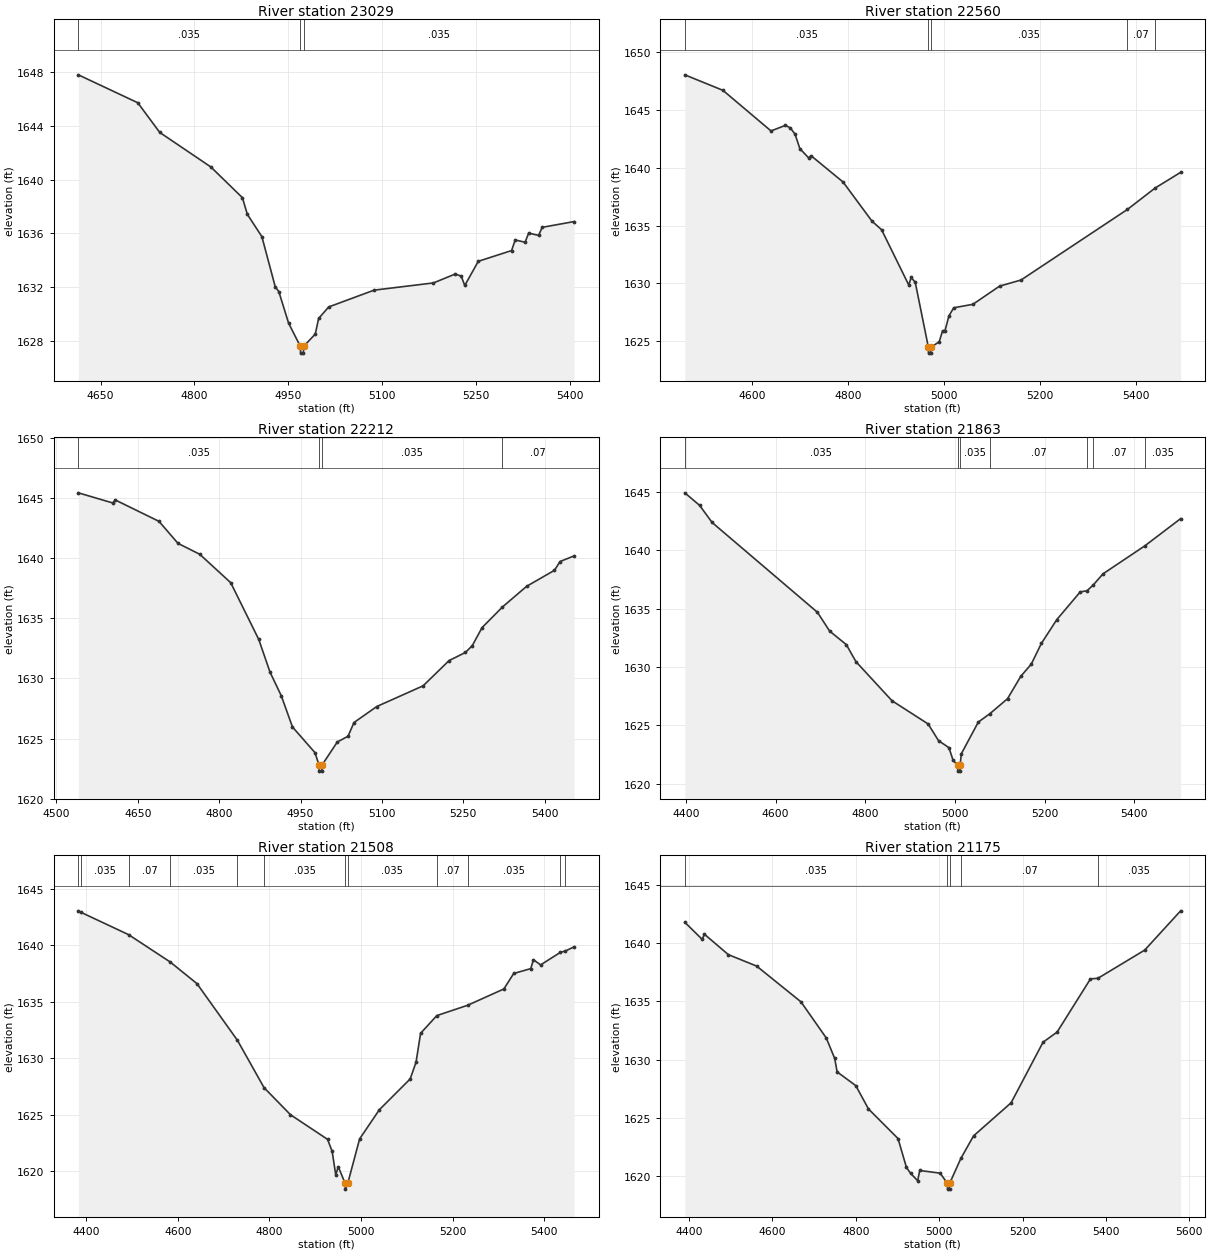
Type RM Length L Ch R = 1,23029,469,469,469
BEGIN DESCRIPTION:
Mapping XS be73f306
END DESCRIPTION:
XS GIS Cut Line= 4
      1640263.63      6965598.81      1640595.26      6965798.48
      1640678.60      6965862.72      1640827.85      6966123.05
#Sta/Elev= 30
  4614.5 1647.81  4709.5 1645.73  4744.6 1643.52  4826.2 1640.95  4876.7 1638.66
  4884.6 1637.42  4907.8 1635.76  4929.1 1632.04  4935.0 1631.65  4950.5 1629.32
  4969.3 1627.58  4969.7 1627.08  4974.1 1627.08  4974.5 1627.58  4993.2 1628.50
  4998.5 1629.66  5014.6 1630.52  5087.1 1631.77  5182.1 1632.31  5216.7 1632.97
  5226.3 1632.82  5232.1 1632.12  5253.7 1633.92  5306.9 1634.72  5312.7 1635.51
  5328.5 1635.34  5334.2 1636.02  5350.1 1635.85  5355.8 1636.45  5406.9 1636.88
#Mann=3,-1,0
  4614.5   0.035       0  4969.3   0.035       0  4974.5   0.035       0
Bank Sta=4969.3,4974.5
Exp/Cntr=0.3,0.1

Type RM Length L Ch R = 1,22560,348,348,348
BEGIN DESCRIPTION:
Mapping XS b0c58bcf
END DESCRIPTION:
XS GIS Cut Line= 3
      1639915.68      6966190.38      1640453.83      6966216.42
      1640946.87      6966244.20
#Sta/Elev= 30
  4460.1 1648.03  4539.5 1646.69  4639.6 1643.18  4669.7 1643.66  4679.7 1643.45
  4689.7 1642.90  4699.7 1641.65  4718.0 1640.85  4723.0 1641.04  4789.8 1638.76
  4849.9 1635.38  4869.9 1634.64  4926.5 1629.86  4931.5 1630.51  4940.0 1630.10
  4967.4 1624.47  4967.8 1623.97  4972.3 1623.97  4972.7 1624.47  4990.0 1624.96
  4997.0 1625.91  5002.0 1625.91  5010.1 1627.18  5020.1 1627.89  5060.1 1628.19
  5115.5 1629.76  5160.3 1630.29  5381.8 1636.39  5439.5 1638.24  5492.7 1639.60
#Mann=5,-1,0
  4460.1   0.035       0  4967.4   0.035       0  4972.7   0.035       0
  5381.8    0.07       0  5439.5   0.035       0
Bank Sta=4967.4,4972.7
Exp/Cntr=0.3,0.1

Type RM Length L Ch R = 1,22212,349,349,349
BEGIN DESCRIPTION:
Mapping XS 396258a5
END DESCRIPTION:
XS GIS Cut Line= 3
      1640113.55      6966650.45      1640557.99      6966532.39
      1641000.35      6966430.04
#Sta/Elev= 30
  4540.3 1645.43  4603.5 1644.59  4608.7 1644.83  4689.0 1643.06  4724.0 1641.23
  4764.2 1640.32  4821.2 1637.96  4872.9 1633.24  4893.6 1630.53  4914.3 1628.57
  4935.0 1625.97  4976.4 1623.84  4984.0 1622.80  4984.5 1622.30  4989.0 1622.30
  4989.4 1622.80  5017.6 1624.72  5037.4 1625.20  5048.4 1626.34  5090.4 1627.67
  5175.8 1629.39  5223.7 1631.49  5253.7 1632.16  5266.4 1632.73  5284.5 1634.23
  5322.0 1635.94  5366.6 1637.66  5417.9 1638.99  5428.2 1639.72  5454.2 1640.19
#Mann=4,-1,0
  4540.3   0.035       0  4984.0   0.035       0  4989.4   0.035       0
  5322.0    0.07       0
Bank Sta=4984,4989.4
Exp/Cntr=0.3,0.1

Type RM Length L Ch R = 1,21863,355,355,355
BEGIN DESCRIPTION:
Mapping XS 1d483d65
END DESCRIPTION:
XS GIS Cut Line= 3
      1640216.59      6967123.21      1640733.09      6966821.56
      1641175.82      6966574.15
#Sta/Elev= 30
  4397.8 1644.91  4430.7 1643.84  4458.7 1642.37  4693.5 1634.68  4720.7 1633.07
  4757.9 1631.91  4779.4 1630.45  4859.6 1627.11  4940.2 1625.12  4963.4 1623.69
  4986.6 1623.09  4995.9 1622.01  5006.0 1621.58  5006.4 1621.08  5011.0 1621.08
  5011.4 1621.58  5014.4 1622.58  5052.1 1625.28  5077.6 1625.99  5117.2 1627.28
  5147.0 1629.21  5170.0 1630.23  5192.6 1632.01  5227.2 1634.06  5279.4 1636.43
  5294.2 1636.52  5308.1 1637.01  5330.3 1637.98  5423.3 1640.37  5503.1 1642.70
#Mann=7,-1,0
  4397.8   0.035       0  5006.0   0.035       0  5011.4   0.035       0
  5077.6    0.07       0  5294.2   0.035       0  5308.1    0.07       0
  5423.3   0.035       0
Bank Sta=5006,5011.4
Exp/Cntr=0.3,0.1

Type RM Length L Ch R = 1,21508,333,333,333
BEGIN DESCRIPTION:
Mapping XS 28f97681
END DESCRIPTION:
XS GIS Cut Line= 3
      1640388.07      6967340.21      1640950.10      6967092.83
      1641353.73      6966856.30
#Sta/Elev= 30
  4383.2 1643.05  4388.3 1642.93  4492.8 1640.94  4583.6 1638.52  4642.1 1636.60
  4730.4 1631.58  4788.4 1627.39  4846.1 1624.99  4927.0 1622.81  4937.1 1621.74
  4944.9 1619.65  4950.3 1620.39  4965.5 1618.90  4965.9 1618.40  4971.0 1618.90
  4997.0 1622.85  5040.0 1625.43  5107.3 1628.16  5120.1 1629.64  5130.0 1632.20
  5165.4 1633.77  5232.4 1634.68  5311.7 1636.13  5333.2 1637.50  5370.4 1637.93
  5376.2 1638.72  5391.9 1638.26  5434.6 1639.36  5446.2 1639.50  5465.1 1639.86
#Mann=12,-1,0
  4383.2    0.07       0  4388.3   0.035       0  4492.8    0.07       0
  4583.6   0.035       0  4730.4    0.07       0  4788.4   0.035       0
  4965.5   0.035       0  4971.0   0.035       0  5165.4    0.07       0
  5232.4   0.035       0  5434.6    0.07       0  5446.2   0.035       0
Bank Sta=4965.5,4971
Exp/Cntr=0.3,0.1

Type RM Length L Ch R = 1,21175,362,362,362
BEGIN DESCRIPTION:
Mapping XS 216b2db8
END DESCRIPTION:
XS GIS Cut Line= 3
      1640429.69      6967459.62      1641028.69      6967365.86
      1641611.05      6967336.40
#Sta/Elev= 30
  4389.7 1641.78  4431.5 1640.31  4436.6 1640.76  4494.2 1639.00  4562.0 1638.02
  4668.4 1634.95  4729.1 1631.85  4749.3 1630.09  4755.1 1628.94  4799.9 1627.76
  4830.3 1625.76  4901.2 1623.22  4921.4 1620.74  4931.5 1620.23  4948.3 1619.60
  4953.3 1620.48  5002.3 1620.25  5019.5 1619.38  5020.0 1618.88  5024.7 1618.88
  5025.1 1619.38  5052.0 1621.52  5082.4 1623.45  5172.5 1626.29  5249.1 1631.49
  5282.7 1632.35  5362.8 1636.92  5380.7 1636.97  5492.9 1639.39  5579.1 1642.76
#Mann=5,-1,0
  4389.7   0.035       0  5019.5   0.035       0  5025.1   0.035       0
  5052.0    0.07       0  5380.7   0.035       0
Bank Sta=5019.5,5025.1
Exp/Cntr=0.3,0.1

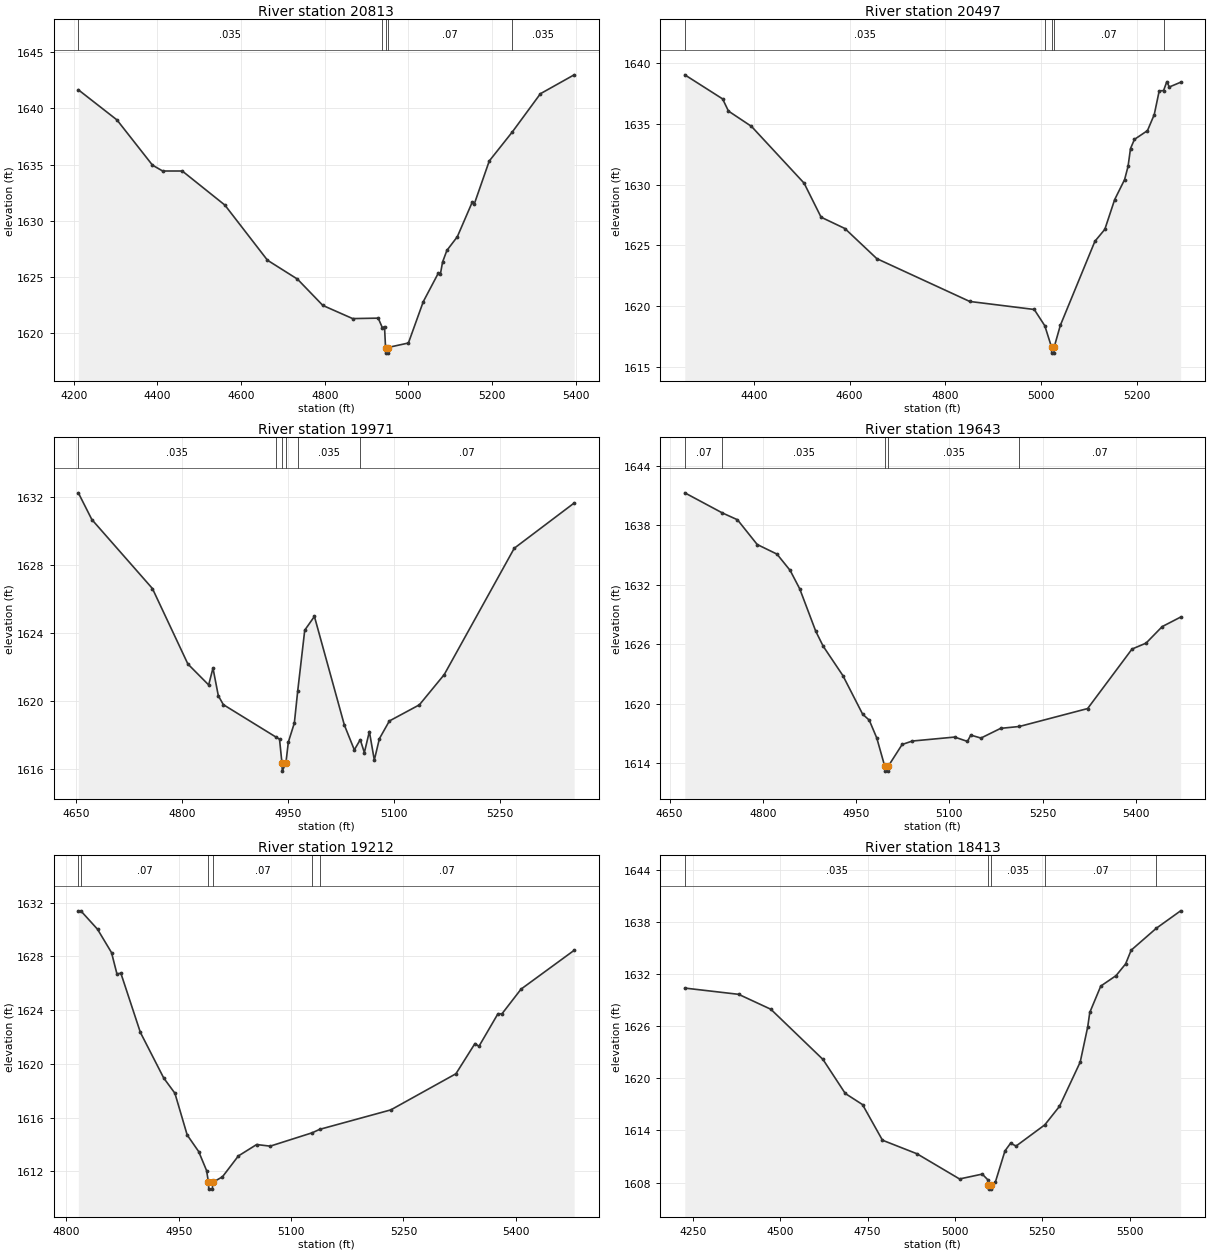
Type RM Length L Ch R = 1,20813,316,316,316
BEGIN DESCRIPTION:
Mapping XS d3bea0c9
END DESCRIPTION:
XS GIS Cut Line= 3
      1640380.85      6967535.30      1641151.26      6967682.88
      1641539.72      6967782.70
#Sta/Elev= 30
  4210.9 1641.66  4303.3 1638.98  4388.2 1634.96  4412.5 1634.44  4459.4 1634.44
  4561.3 1631.41  4663.1 1626.51  4734.8 1624.83  4795.5 1622.49  4866.8 1621.32
  4927.9 1621.36  4937.8 1620.51  4943.0 1620.61  4945.4 1618.75  4945.9 1618.25
  4950.6 1618.25  4951.0 1618.75  5000.1 1619.15  5035.7 1622.83  5071.2 1625.33
  5076.4 1625.24  5081.8 1626.35  5092.1 1627.38  5117.1 1628.60  5152.7 1631.67
  5157.9 1631.54  5193.4 1635.33  5248.9 1637.93  5315.7 1641.31  5396.4 1642.99
#Mann=5,-1,0
  4210.9   0.035       0  4937.8    0.07       0  4945.4    0.07       0
  4951.0    0.07       0  5248.9   0.035       0
Bank Sta=4945.4,4951
Exp/Cntr=0.3,0.1

Type RM Length L Ch R = 1,20497,526,526,526
BEGIN DESCRIPTION:
Mapping XS 4980200d
END DESCRIPTION:
XS GIS Cut Line= 3
      1640339.67      6967693.74      1641034.07      6967956.31
      1641318.36      6968030.10
#Sta/Elev= 30
  4255.8 1639.03  4334.8 1637.05  4347.0 1636.05  4395.1 1634.79  4505.1 1630.12
  4540.6 1627.32  4590.3 1626.39  4657.1 1623.91  4851.2 1620.39  4986.0 1619.73
  5008.1 1618.39  5022.1 1616.64  5022.5 1616.14  5027.2 1616.14  5027.7 1616.64
  5040.5 1618.42  5112.8 1625.34  5133.5 1626.32  5154.1 1628.77  5174.8 1630.41
  5182.0 1631.49  5187.2 1632.97  5195.4 1633.72  5222.6 1634.44  5236.8 1635.76
  5247.1 1637.70  5256.3 1637.74  5263.1 1638.47  5268.3 1638.03  5291.9 1638.42
#Mann=5,-1,0
  4255.8   0.035       0  5008.1    0.07       0  5022.1   0.035       0
  5027.7    0.07       0  5256.3   0.035       0
Bank Sta=5022.1,5027.7
Exp/Cntr=0.3,0.1

Type RM Length L Ch R = 1,19971,328,328,328
BEGIN DESCRIPTION:
Mapping XS 5b694118
END DESCRIPTION:
XS GIS Cut Line= 3
      1640398.60      6967857.78      1640604.75      6968140.96
      1640850.12      6968392.82
#Sta/Elev= 30
  4653.5 1632.23  4672.6 1630.66  4758.4 1626.60  4808.6 1622.16  4838.0 1620.93
  4844.1 1621.92  4851.7 1620.29  4858.8 1619.77  4933.4 1617.86  4938.3 1617.74
  4941.7 1616.36  4942.2 1615.86  4947.4 1616.36  4950.8 1617.57  4959.3 1618.69
  4964.0 1620.55  4974.0 1624.15  4987.7 1624.96  5030.1 1618.57  5044.2 1617.11
  5052.6 1617.71  5058.4 1616.95  5065.5 1618.19  5072.5 1616.51  5079.7 1617.77
  5093.8 1618.81  5136.3 1619.76  5171.5 1621.54  5270.6 1628.97  5355.4 1631.63
#Mann=6,-1,0
  4653.5   0.035       0  4933.4    0.07       0  4941.7   0.035       0
  4947.4    0.07       0  4964.0   0.035       0  5052.6    0.07       0
Bank Sta=4941.7,4947.4
Exp/Cntr=0.3,0.1

Type RM Length L Ch R = 1,19643,431,431,431
BEGIN DESCRIPTION:
Mapping XS 36050033
END DESCRIPTION:
XS GIS Cut Line= 3
      1640015.13      6968161.78      1640322.41      6968269.85
      1640769.02      6968422.19
#Sta/Elev= 30
  4674.4 1641.29  4734.8 1639.26  4759.1 1638.57  4790.9 1636.07  4822.7 1635.10
  4843.9 1633.45  4859.3 1631.59  4885.0 1627.32  4896.9 1625.81  4928.7 1622.83
  4960.5 1618.93  4971.1 1618.33  4983.2 1616.53  4996.0 1613.68  4996.4 1613.18
  5001.2 1613.18  5001.7 1613.68  5024.0 1615.87  5040.4 1616.22  5108.5 1616.62
  5129.1 1616.18  5134.4 1616.82  5150.8 1616.52  5182.5 1617.50  5212.6 1617.69
  5322.4 1619.50  5393.8 1625.51  5416.4 1626.11  5442.4 1627.78  5472.0 1628.74
#Mann=5,-1,0
  4674.4    0.07       0  4734.8   0.035       0  4996.0   0.035       0
  5001.7   0.035       0  5212.6    0.07       0
Bank Sta=4996,5001.7
Exp/Cntr=0.3,0.1

Type RM Length L Ch R = 1,19212,799,799,799
BEGIN DESCRIPTION:
Mapping XS e198e3c0
END DESCRIPTION:
XS GIS Cut Line= 3
      1640153.12      6968720.37      1640323.71      6968661.77
      1640776.79      6968499.03
#Sta/Elev= 30
  4816.1 1631.40  4819.4 1631.40  4841.7 1630.03  4860.4 1628.29  4867.6 1626.71
  4872.9 1626.75  4898.9 1622.35  4930.1 1618.95  4945.0 1617.82  4961.4 1614.71
  4976.7 1613.48  4987.3 1612.06  4989.8 1611.18  4990.2 1610.68  4995.0 1610.68
  4995.5 1611.18  5008.5 1611.60  5029.7 1613.15  5054.1 1614.00  5072.2 1613.88
  5128.5 1614.88  5138.2 1615.13  5233.2 1616.58  5320.1 1619.27  5345.5 1621.52
  5350.8 1621.31  5376.2 1623.74  5381.5 1623.73  5407.0 1625.57  5477.9 1628.46
#Mann=6,-1,0
  4816.1   0.035       0  4819.4    0.07       0  4989.8    0.07       0
  4995.5    0.07       0  5128.5   0.035       0  5138.2    0.07       0
Bank Sta=4989.8,4995.5
Exp/Cntr=0.3,0.1

Type RM Length L Ch R = 1,18413,478,478,478
BEGIN DESCRIPTION:
Mapping XS c6c0c44d
END DESCRIPTION:
XS GIS Cut Line= 3
      1639972.84      6968832.90      1640563.12      6969336.38
      1640879.09      6969897.15
#Sta/Elev= 30
  4226.5 1630.38  4380.6 1629.66  4472.9 1627.94  4622.2 1622.16  4685.9 1618.25
  4735.3 1616.97  4792.4 1612.87  4891.2 1611.31  5013.1 1608.41  5078.1 1608.97
  5094.1 1608.31  5095.5 1607.74  5096.0 1607.24  5103.7 1607.24  5104.2 1607.74
  5115.7 1608.06  5143.1 1611.64  5159.1 1612.52  5175.0 1612.20  5257.2 1614.64
  5299.2 1616.77  5358.5 1621.86  5380.1 1625.93  5385.9 1627.57  5417.4 1630.61
  5461.1 1631.81  5488.5 1633.16  5504.4 1634.74  5576.6 1637.27  5646.0 1639.27
#Mann=5,-1,0
  4226.5   0.035       0  5095.5   0.035       0  5104.2   0.035       0
  5257.2    0.07       0  5576.6   0.035       0
Bank Sta=5095.5,5104.2
Exp/Cntr=0.3,0.1

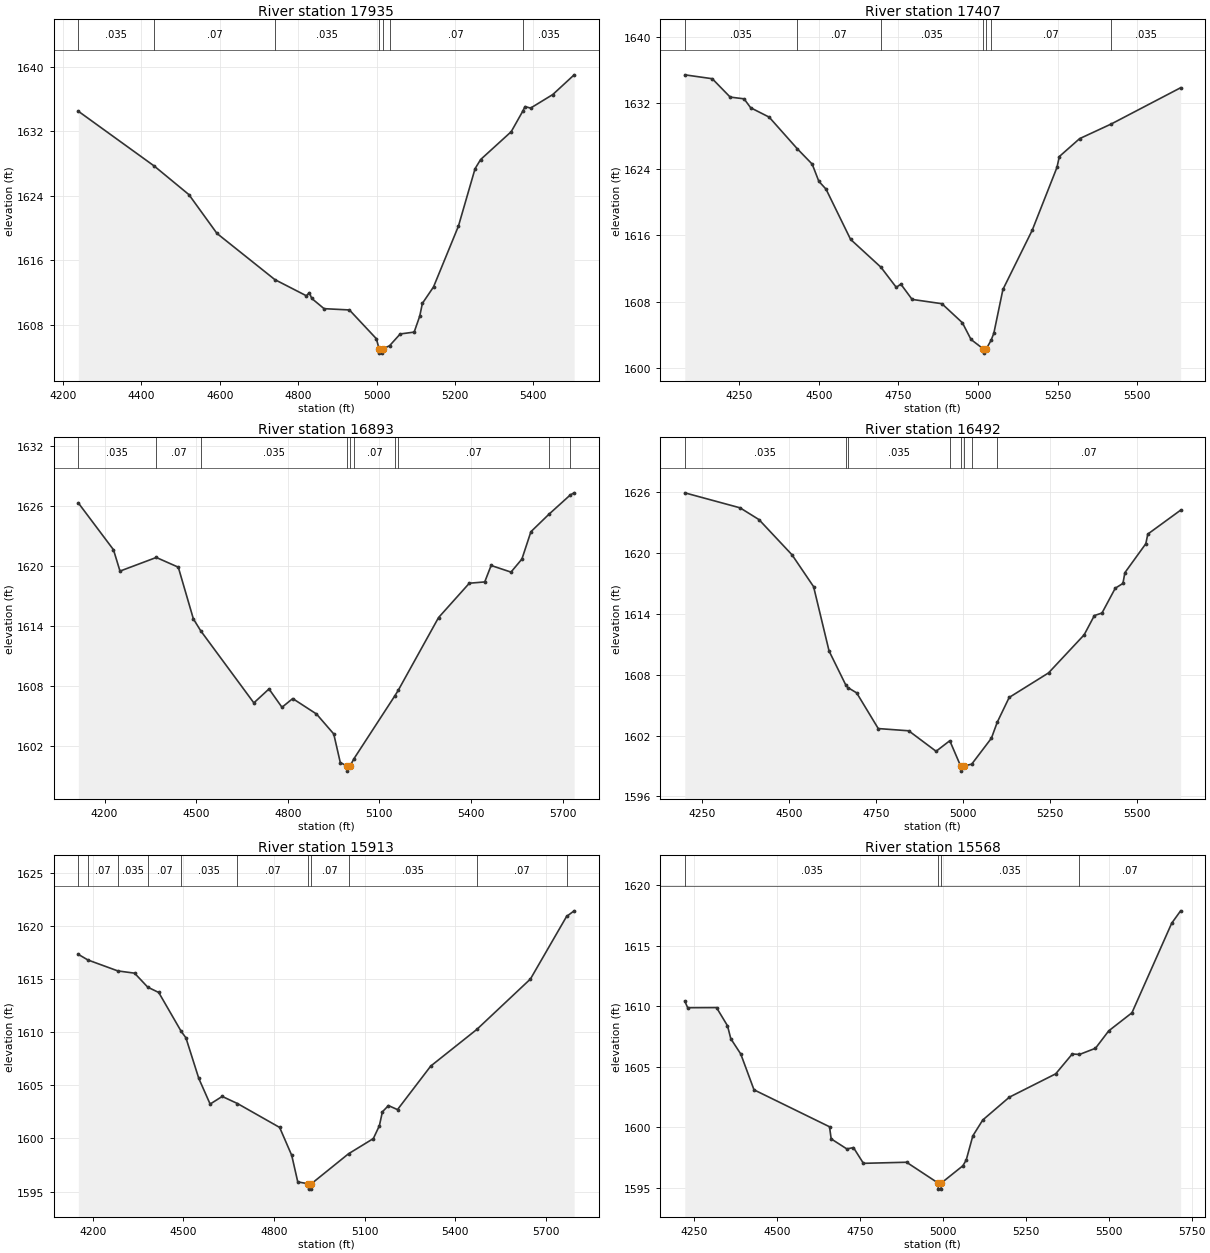
Type RM Length L Ch R = 1,17935,528,528,528
BEGIN DESCRIPTION:
Mapping XS ed8ce09b
END DESCRIPTION:
XS GIS Cut Line= 3
      1639690.31      6969358.70      1640349.99      6969737.15
      1640696.17      6970104.10
#Sta/Elev= 30
  4239.1 1634.51  4432.4 1627.72  4521.2 1624.16  4592.8 1619.34  4740.4 1613.61
  4820.9 1611.60  4828.6 1611.99  4834.4 1611.28  4866.0 1610.00  4930.7 1609.84
  4999.6 1606.26  5006.5 1604.98  5007.0 1604.48  5014.8 1604.48  5015.3 1604.98
  5033.2 1605.40  5060.3 1606.86  5095.9 1607.09  5110.1 1609.07  5116.9 1610.66
  5145.3 1612.70  5208.8 1620.24  5251.3 1627.38  5265.4 1628.51  5343.5 1631.97
  5373.0 1634.52  5378.7 1635.09  5392.9 1634.90  5449.5 1636.58  5504.1 1639.03
#Mann=7,-1,0
  4239.1   0.035       0  4432.4    0.07       0  4740.4   0.035       0
  5006.5   0.035       0  5015.3   0.035       0  5033.2    0.07       0
  5373.0   0.035       0
Bank Sta=5006.5,5015.3
Exp/Cntr=0.3,0.1

Type RM Length L Ch R = 1,17407,514,514,514
BEGIN DESCRIPTION:
Mapping XS 5c418d3f
END DESCRIPTION:
XS GIS Cut Line= 3
      1639263.21      6969539.25      1639992.35      6970098.26
      1640466.74      6970524.17
#Sta/Elev= 30
  4079.7 1635.41  4165.9 1634.94  4222.1 1632.72  4265.7 1632.51  4286.5 1631.43
  4344.5 1630.30  4432.7 1626.48  4479.6 1624.62  4500.4 1622.55  4523.0 1621.60
  4600.1 1615.53  4695.3 1612.17  4743.4 1609.74  4757.9 1610.12  4793.2 1608.28
  4886.7 1607.76  4951.0 1605.46  4978.1 1603.44  5016.9 1602.29  5017.4 1601.79
  5025.8 1602.29  5041.2 1603.35  5049.8 1604.21  5078.2 1609.48  5170.1 1616.63
  5247.9 1624.23  5255.3 1625.54  5318.9 1627.70  5418.7 1629.48  5636.0 1633.85
#Mann=7,-1,0
  4079.7   0.035       0  4432.7    0.07       0  4695.3   0.035       0
  5016.9   0.035       0  5025.8   0.035       0  5041.2    0.07       0
  5418.7   0.035       0
Bank Sta=5016.9,5025.8
Exp/Cntr=0.3,0.1

Type RM Length L Ch R = 1,16893,401,401,401
BEGIN DESCRIPTION:
Mapping XS 967e67a6
END DESCRIPTION:
XS GIS Cut Line= 3
      1638976.72      6969813.53      1639612.15      6970431.59
      1640039.24      6971032.30
#Sta/Elev= 30
  4114.1 1626.30  4229.2 1621.63  4250.5 1619.50  4369.4 1620.86  4441.4 1619.89
  4490.8 1614.73  4514.9 1613.54  4688.8 1606.35  4738.4 1607.74  4780.9 1605.91
  4816.1 1606.78  4893.9 1605.24  4950.4 1603.25  4971.8 1600.40  4994.5 1600.04
  4995.0 1599.54  5003.5 1600.04  5016.8 1600.79  5150.8 1607.07  5161.3 1607.59
  5293.5 1614.86  5394.3 1618.29  5444.8 1618.42  5465.7 1620.06  5530.8 1619.40
  5566.5 1620.70  5596.0 1623.43  5654.6 1625.16  5725.4 1627.11  5737.6 1627.31
#Mann=10,-1,0
  4114.1   0.035       0  4369.4    0.07       0  4514.9   0.035       0
  4994.5   0.035       0  5003.5   0.035       0  5016.8    0.07       0
  5150.8   0.035       0  5161.3    0.07       0  5654.6   0.035       0
  5725.4    0.07       0
Bank Sta=4994.5,5003.5
Exp/Cntr=0.3,0.1

Type RM Length L Ch R = 1,16492,579,579,579
BEGIN DESCRIPTION:
Mapping XS a733d8e0
END DESCRIPTION:
XS GIS Cut Line= 3
      1638573.96      6970448.96      1639328.33      6970714.67
      1639879.40      6971009.53
#Sta/Elev= 30
  4200.2 1625.95  4359.0 1624.47  4413.3 1623.31  4508.4 1619.83  4570.3 1616.69
  4614.8 1610.34  4662.8 1606.99  4668.6 1606.74  4694.1 1606.21  4756.1 1602.69
  4843.6 1602.47  4922.3 1600.45  4961.7 1601.49  4992.9 1598.99  4993.4 1598.49
  5002.0 1598.99  5024.7 1599.18  5081.3 1601.74  5098.0 1603.31  5132.3 1605.76
  5245.4 1608.18  5347.8 1611.94  5377.1 1613.84  5399.0 1614.09  5437.2 1616.54
  5459.2 1617.01  5464.8 1618.07  5525.0 1620.93  5530.7 1621.88  5625.0 1624.24
#Mann=8,-1,0
  4200.2   0.035       0  4662.8    0.07       0  4668.6   0.035       0
  4961.7    0.07       0  4992.9    0.07       0  5002.0    0.07       0
  5024.7   0.035       0  5098.0    0.07       0
Bank Sta=4992.9,5002
Exp/Cntr=0.3,0.1

Type RM Length L Ch R = 1,15913,345,345,345
BEGIN DESCRIPTION:
Mapping XS c4c9125e
END DESCRIPTION:
XS GIS Cut Line= 3
      1638079.03      6971040.79      1638924.56      6971066.84
      1639719.71      6971072.04
#Sta/Elev= 30
  4152.5 1617.34  4184.3 1616.81  4283.3 1615.78  4338.6 1615.57  4382.3 1614.25
  4418.6 1613.75  4492.9 1610.09  4508.6 1609.48  4551.3 1605.65  4588.7 1603.24
  4628.7 1603.96  4679.3 1603.29  4818.8 1601.04  4858.8 1598.41  4878.8 1595.91
  4914.2 1595.73  4914.7 1595.23  4923.0 1595.23  4923.5 1595.73  5046.8 1598.56
  5128.9 1599.99  5148.9 1601.20  5158.9 1602.51  5178.9 1603.10  5208.9 1602.72
  5318.9 1606.82  5471.4 1610.27  5648.9 1615.02  5768.5 1620.91  5793.6 1621.44
#Mann=11,-1,0
  4152.5   0.035       0  4184.3    0.07       0  4283.3   0.035       0
  4382.3    0.07       0  4492.9   0.035       0  4679.3    0.07       0
  4914.2    0.07       0  4923.5    0.07       0  5046.8   0.035       0
  5471.4    0.07       0  5768.5   0.035       0
Bank Sta=4914.2,4923.5
Exp/Cntr=0.3,0.1

Type RM Length L Ch R = 1,15568,835,835,835
BEGIN DESCRIPTION:
Mapping XS 59979811
END DESCRIPTION:
XS GIS Cut Line= 3
      1637926.29      6971250.14      1638704.86      6971272.94
      1639421.86      6971272.10
#Sta/Elev= 30
  4221.1 1610.41  4229.8 1609.87  4316.8 1609.88  4349.9 1608.38  4359.9 1607.31
  4389.9 1606.05  4429.9 1603.09  4657.7 1600.04  4662.7 1599.04  4710.0 1598.21
  4730.0 1598.32  4760.0 1597.02  4890.1 1597.11  4985.5 1595.39  4986.0 1594.89
  4994.3 1594.89  4994.8 1595.39  5060.1 1596.82  5070.1 1597.29  5090.1 1599.29
  5120.1 1600.60  5200.1 1602.48  5340.1 1604.41  5390.1 1606.05  5411.8 1606.01
  5460.1 1606.52  5500.1 1607.96  5570.1 1609.45  5690.1 1616.85  5717.0 1617.87
#Mann=4,-1,0
  4221.1   0.035       0  4985.5   0.035       0  4994.8   0.035       0
  5411.8    0.07       0
Bank Sta=4985.5,4994.8
Exp/Cntr=0.3,0.1