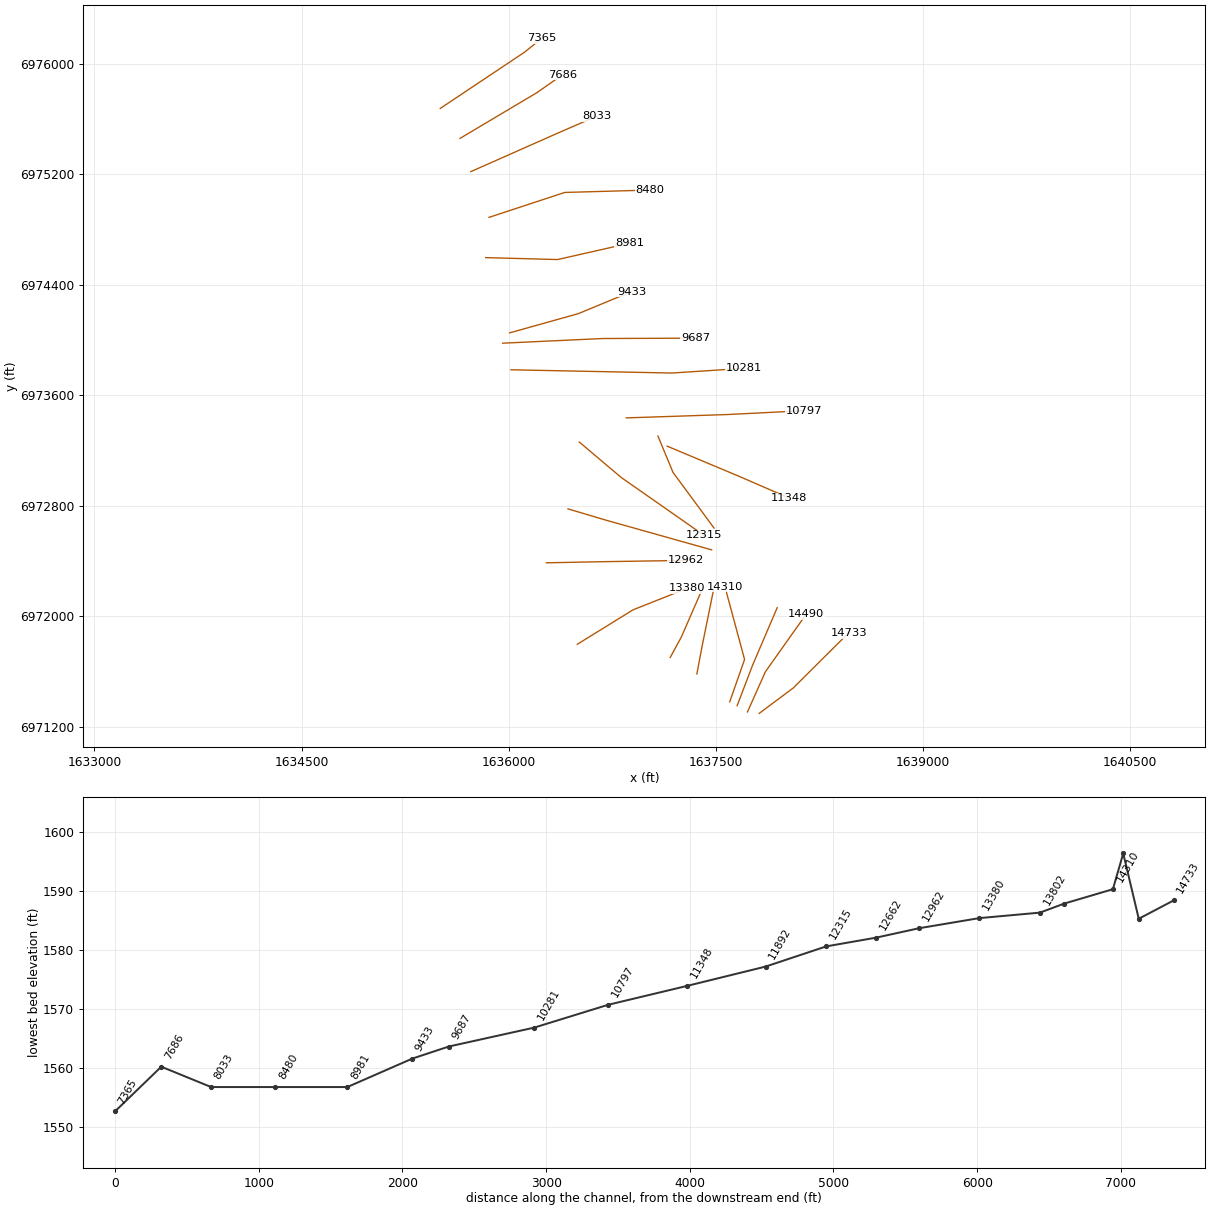
HEC-RAS study Hog Creek.prj: Hog Creek Base Level Engineering

--- Hog Creek.g01 (geometry) --- (continued)

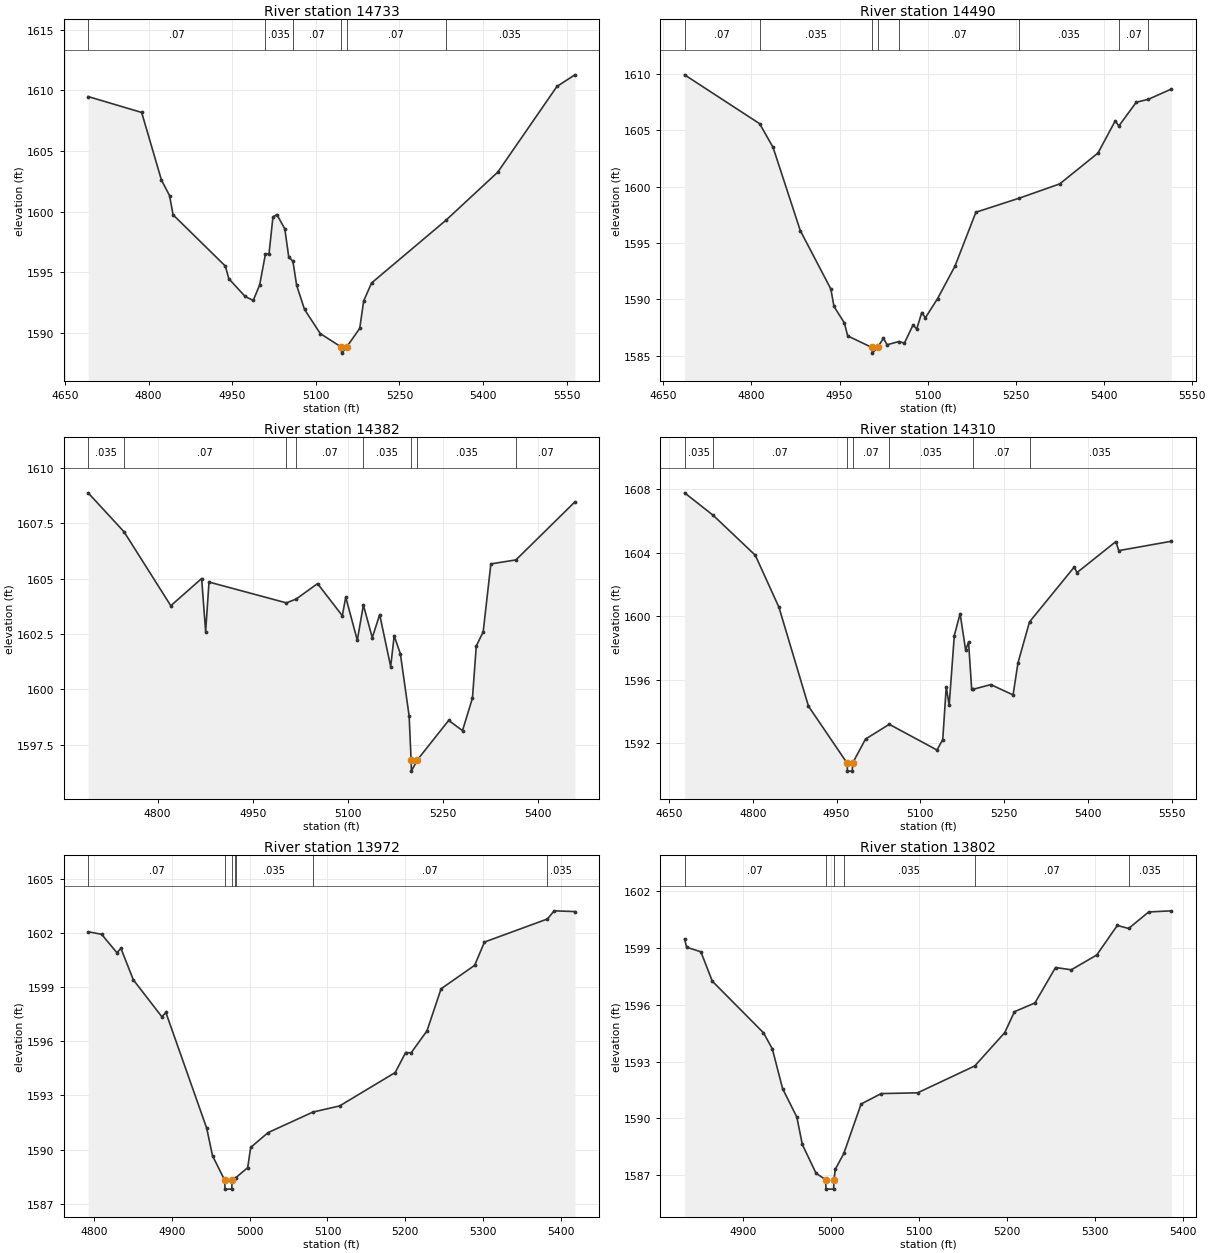
Type RM Length L Ch R = 1,14733,243,243,243
BEGIN DESCRIPTION:
Mapping XS feea4b1d
END DESCRIPTION:
XS GIS Cut Line= 3
      1637813.47      6971295.29      1638059.98      6971479.31
      1638460.49      6971878.09
#Sta/Elev= 30
  4691.7 1609.48  4787.7 1608.17  4823.1 1602.61  4837.7 1601.32  4844.0 1599.74
  4937.8 1595.51  4944.0 1594.47  4973.2 1593.01  4987.8 1592.68  4999.3 1593.97
  5009.6 1596.49  5016.1 1596.54  5023.1 1599.56  5030.2 1599.76  5044.4 1598.57
  5051.4 1596.27  5058.9 1595.91  5065.6 1593.93  5079.7 1591.94  5108.0 1589.95
  5145.7 1588.84  5146.2 1588.34  5155.2 1588.84  5178.7 1590.38  5185.8 1592.64
  5199.9 1594.12  5333.1 1599.28  5426.2 1603.25  5532.3 1610.31  5564.5 1611.27
#Mann=6,-1,0
  4691.7    0.07       0  5009.6   0.035       0  5058.9    0.07       0
  5145.7    0.07       0  5155.2    0.07       0  5333.1   0.035       0
Bank Sta=5145.7,5155.2
Exp/Cntr=0.3,0.1

Type RM Length L Ch R = 1,14490,108,108,108
BEGIN DESCRIPTION:
Mapping XS 6520f811
END DESCRIPTION:
XS GIS Cut Line= 3
      1637728.40      6971305.74      1637858.59      6971597.36
      1638153.34      6972013.48
#Sta/Elev= 30
  4686.1 1609.90  4813.9 1605.57  4836.8 1603.47  4883.2 1596.09  4935.2 1590.92
  4940.6 1589.37  4958.4 1587.90  4963.9 1586.76  5005.3 1585.73  5005.8 1585.23
  5014.9 1585.73  5024.9 1586.56  5031.0 1585.97  5051.3 1586.26  5060.6 1586.12
  5075.4 1587.74  5081.5 1587.36  5090.2 1588.83  5096.3 1588.36  5117.2 1590.07
  5146.7 1592.94  5182.4 1597.72  5256.4 1598.97  5325.2 1600.23  5390.4 1602.97
  5419.9 1605.83  5425.9 1605.36  5455.6 1607.47  5476.2 1607.73  5515.4 1608.64
#Mann=8,-1,0
  4686.1    0.07       0  4813.9   0.035       0  5005.3   0.035       0
  5014.9   0.035       0  5051.3    0.07       0  5256.4   0.035       0
  5425.9    0.07       0  5476.2   0.035       0
Bank Sta=5005.3,5014.9
Exp/Cntr=0.3,0.1

Type RM Length L Ch R = 1,14382,72,72,72
BEGIN DESCRIPTION:
Mapping XS c329660f
END DESCRIPTION:
XS GIS Cut Line= 3
      1637653.73      6971350.85      1637764.84      6971642.50
      1637943.65      6972060.89
#Sta/Elev= 30
  4690.5 1608.88  4747.1 1607.12  4820.8 1603.78  4869.4 1605.01  4875.7 1602.61
  4881.0 1604.85  5002.9 1603.91  5018.2 1604.08  5052.1 1604.78  5091.1 1603.33
  5096.5 1604.17  5114.7 1602.22  5124.3 1603.81  5138.3 1602.34  5150.0 1603.38
  5167.3 1601.03  5172.8 1602.42  5182.6 1601.61  5196.4 1598.80  5199.5 1596.81
  5200.0 1596.31  5209.1 1596.81  5258.7 1598.60  5280.5 1598.14  5296.2 1599.61
  5302.2 1601.96  5313.1 1602.60  5325.2 1605.67  5364.7 1605.85  5457.6 1608.47
#Mann=8,-1,0
  4690.5   0.035       0  4747.1    0.07       0  5002.9   0.035       0
  5018.2    0.07       0  5124.3   0.035       0  5199.5    0.07       0
  5209.1   0.035       0  5364.7    0.07       0
Bank Sta=5199.5,5209.1
Exp/Cntr=0.3,0.1

Type RM Length L Ch R = 1,14310,338,338,338
BEGIN DESCRIPTION:
Mapping XS 5df45abe
END DESCRIPTION:
XS GIS Cut Line= 3
      1637599.90      6971378.60      1637707.55      6971685.90
      1637565.28      6972213.34
#Sta/Elev= 30
  4677.8 1607.77  4729.1 1606.35  4804.4 1603.84  4846.7 1600.57  4899.7 1594.33
  4969.0 1590.74  4969.5 1590.24  4978.1 1590.24  4978.6 1590.74  5001.9 1592.26
  5044.4 1593.19  5129.9 1591.57  5140.2 1592.23  5146.5 1595.56  5151.7 1594.38
  5160.9 1598.78  5171.3 1600.16  5181.2 1597.86  5186.4 1598.37  5192.0 1595.42
  5195.0 1595.40  5226.3 1595.69  5266.2 1595.04  5274.9 1597.05  5295.6 1599.64
  5375.6 1603.09  5380.8 1602.75  5450.3 1604.70  5455.5 1604.13  5549.7 1604.72
#Mann=7,-1,0
  4677.8   0.035       0  4729.1    0.07       0  4969.0    0.07       0
  4978.6    0.07       0  5044.4   0.035       0  5195.0    0.07       0
  5295.6   0.035       0
Bank Sta=4969,4978.6
Exp/Cntr=0.3,0.1

Type RM Length L Ch R = 1,13972,170,170,170
BEGIN DESCRIPTION:
Mapping XS 5ebd2ca7
END DESCRIPTION:
XS GIS Cut Line= 3
      1637362.35      6971581.00      1637401.41      6971789.32
      1637483.67      6972194.09
#Sta/Elev= 30
  4792.7 1602.07  4810.0 1601.93  4829.7 1600.91  4834.8 1601.15  4850.7 1599.41
  4887.4 1597.36  4892.5 1597.60  4945.0 1591.18  4952.4 1589.66  4968.0 1588.31
  4968.5 1587.81  4977.1 1587.81  4977.6 1588.31  4980.8 1588.40  4982.2 1588.44
  4997.6 1589.00  5001.4 1590.12  5023.7 1590.94  5081.3 1592.08  5115.6 1592.42
  5187.0 1594.27  5200.4 1595.38  5207.4 1595.36  5227.8 1596.58  5245.9 1598.91
  5289.0 1600.21  5301.6 1601.50  5382.5 1602.78  5391.1 1603.23  5417.7 1603.19
#Mann=7,-1,0
  4792.7    0.07       0  4968.0   0.035       0  4977.6    0.07       0
  4980.8    0.07       0  4982.2   0.035       0  5081.3    0.07       0
  5382.5   0.035       0
Bank Sta=4968,4977.6
Exp/Cntr=0.3,0.1

Type RM Length L Ch R = 1,13802,422,422,422
BEGIN DESCRIPTION:
Mapping XS 6d15294d
END DESCRIPTION:
XS GIS Cut Line= 3
      1637169.22      6971700.37      1637249.50      6971847.91
      1637403.58      6972201.64
#Sta/Elev= 30
  4833.5 1599.46  4835.8 1599.03  4852.0 1598.79  4865.0 1597.24  4923.2 1594.52
  4933.3 1593.67  4945.0 1591.57  4961.2 1590.07  4967.4 1588.63  4983.0 1587.11
  4993.9 1586.77  4994.4 1586.27  5003.0 1586.27  5003.5 1586.77  5004.9 1587.31
  5014.7 1588.16  5034.3 1590.76  5057.2 1591.31  5098.6 1591.35  5163.7 1592.77
  5197.8 1594.53  5208.8 1595.63  5232.1 1596.09  5255.5 1597.96  5273.5 1597.84
  5302.4 1598.62  5325.8 1600.18  5338.7 1600.02  5361.5 1600.89  5387.3 1600.95
#Mann=6,-1,0
  4833.5    0.07       0  4993.9    0.07       0  5003.5    0.07       0
  5014.7   0.035       0  5163.7    0.07       0  5338.7   0.035       0
Bank Sta=4993.9,5003.5
Exp/Cntr=0.3,0.1

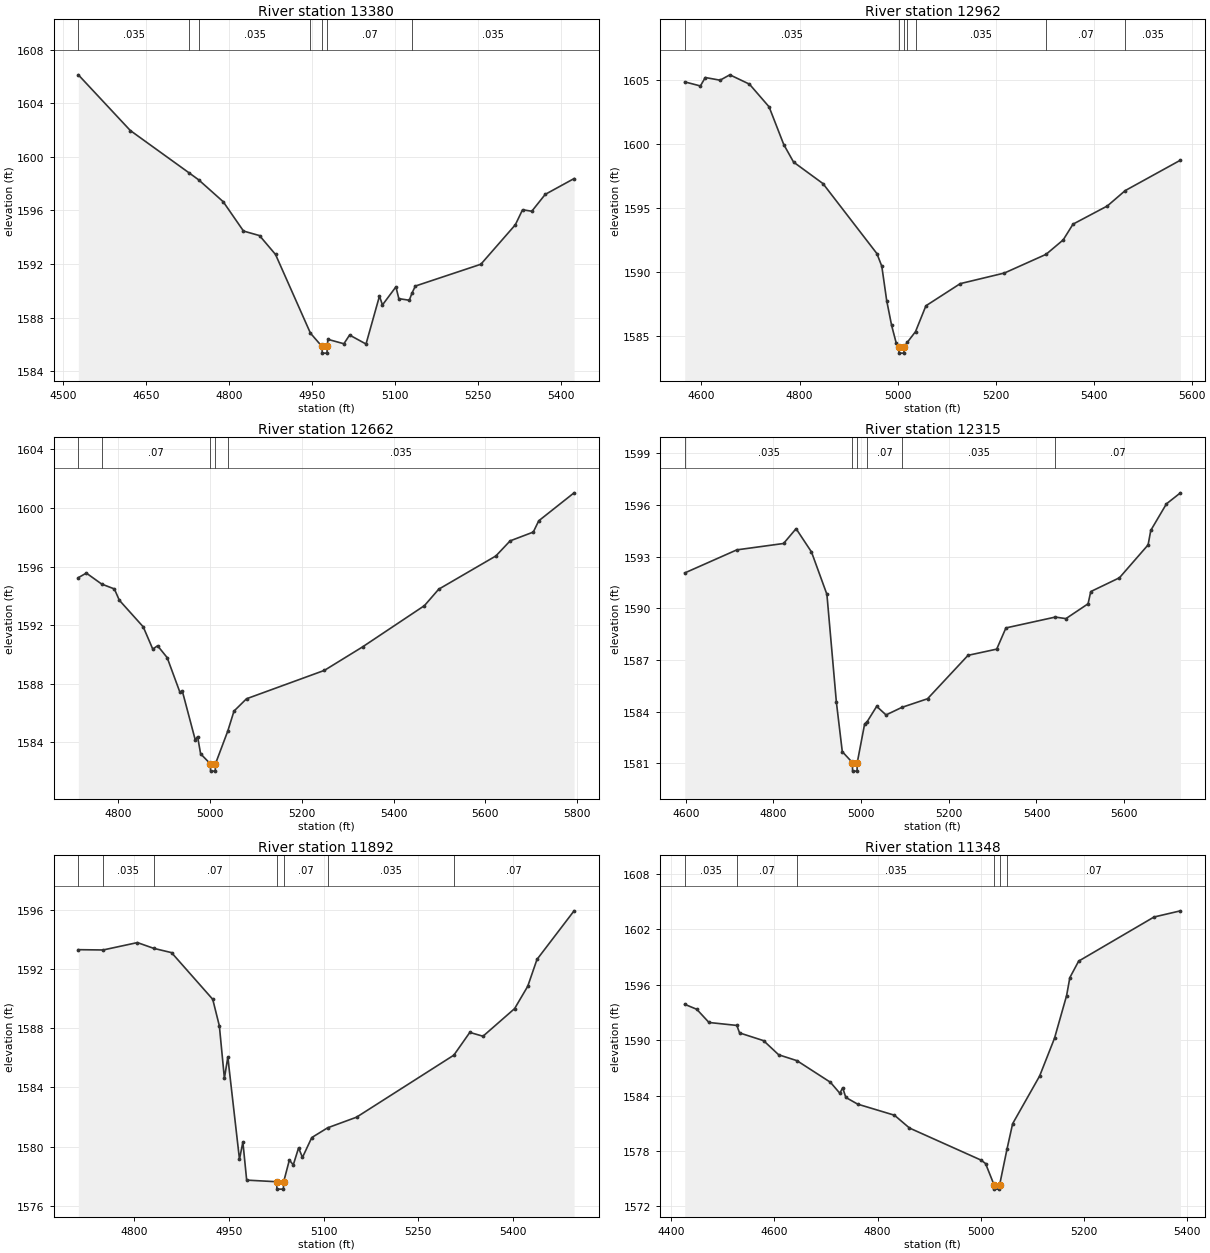
Type RM Length L Ch R = 1,13380,418,418,418
BEGIN DESCRIPTION:
Mapping XS 16228500
END DESCRIPTION:
XS GIS Cut Line= 3
      1636496.51      6971795.86      1636900.11      6972045.40
      1637291.47      6972201.07
#Sta/Elev= 30
  4527.5 1606.13  4621.4 1601.97  4726.8 1598.83  4744.8 1598.29  4789.3 1596.65
  4825.9 1594.46  4854.9 1594.12  4883.8 1592.71  4946.9 1586.83  4967.7 1585.84
  4968.2 1585.34  4976.8 1585.34  4977.3 1585.84  4978.4 1586.37  5007.3 1586.04
  5017.6 1586.69  5047.3 1586.02  5071.6 1589.60  5077.0 1588.94  5101.3 1590.29
  5106.6 1589.41  5125.5 1589.29  5130.2 1589.81  5136.4 1590.35  5254.8 1591.98
  5317.1 1594.93  5330.1 1596.05  5346.8 1595.94  5371.1 1597.20  5423.2 1598.38
#Mann=7,-1,0
  4527.5   0.035       0  4726.8    0.07       0  4744.8   0.035       0
  4946.9    0.07       0  4967.7    0.07       0  4977.3    0.07       0
  5130.2   0.035       0
Bank Sta=4967.7,4977.3
Exp/Cntr=0.3,0.1

Type RM Length L Ch R = 1,12962,300,300,300
BEGIN DESCRIPTION:
Mapping XS 636bb337
END DESCRIPTION:
XS GIS Cut Line= 3
      1636272.96      6972386.11      1636709.14      6972394.79
      1637284.21      6972403.47
#Sta/Elev= 30
  4565.8 1604.83  4597.8 1604.51  4607.8 1605.17  4637.9 1604.96  4657.9 1605.38
  4697.9 1604.65  4737.9 1602.88  4767.9 1599.93  4787.9 1598.56  4847.9 1596.88
  4957.9 1591.41  4967.9 1590.42  4977.9 1587.73  4987.9 1585.80  4997.5 1584.39
  5002.4 1584.13  5002.9 1583.63  5013.0 1583.63  5013.5 1584.13  5020.2 1584.49
  5036.7 1585.31  5057.9 1587.33  5127.9 1589.06  5218.0 1589.89  5303.0 1591.35
  5338.0 1592.48  5358.0 1593.71  5428.0 1595.13  5464.4 1596.33  5577.2 1598.71
#Mann=7,-1,0
  4565.8   0.035       0  5002.4   0.035       0  5013.5   0.035       0
  5020.2    0.07       0  5036.7   0.035       0  5303.0    0.07       0
  5464.4   0.035       0
Bank Sta=5002.4,5013.5
Exp/Cntr=0.3,0.1

Type RM Length L Ch R = 1,12662,347,347,347
BEGIN DESCRIPTION:
Mapping XS 41ecd902
END DESCRIPTION:
XS GIS Cut Line= 3
      1636429.32      6972776.81      1636703.58      6972695.22
      1637469.25      6972479.93
#Sta/Elev= 30
  4712.4 1595.24  4729.9 1595.55  4763.4 1594.80  4791.0 1594.47  4801.8 1593.70
  4854.0 1591.88  4874.8 1590.36  4885.3 1590.59  4906.2 1589.78  4934.2 1587.40
  4939.4 1587.48  4967.4 1584.17  4972.6 1584.38  4979.2 1583.21  5000.4 1582.53
  5000.9 1582.03  5011.1 1582.03  5011.6 1582.53  5038.6 1584.78  5052.0 1586.13
  5079.3 1586.97  5249.3 1588.91  5332.4 1590.51  5467.5 1593.33  5498.6 1594.45
  5623.3 1596.72  5654.4 1597.75  5704.9 1598.35  5716.8 1599.12  5793.9 1601.03
#Mann=5,-1,0
  4712.4   0.035       0  4763.4    0.07       0  5000.4    0.07       0
  5011.6    0.07       0  5038.6   0.035       0
Bank Sta=5000.4,5011.6
Exp/Cntr=0.3,0.1

Type RM Length L Ch R = 1,12315,423,423,423
BEGIN DESCRIPTION:
Mapping XS 0e685ba6
END DESCRIPTION:
XS GIS Cut Line= 3
      1636510.84      6973261.22      1636814.69      6973004.25
      1637415.40      6972584.10
#Sta/Elev= 30
  4597.5 1592.05  4716.4 1593.39  4823.0 1593.76  4851.6 1594.62  4886.7 1593.27
  4921.9 1590.81  4943.5 1584.56  4957.0 1581.68  4980.0 1581.05  4980.5 1580.55
  4990.7 1580.55  4991.2 1581.05  5008.0 1583.29  5013.5 1583.41  5035.5 1584.31
  5056.8 1583.81  5093.0 1584.25  5151.5 1584.75  5243.9 1587.27  5309.3 1587.63
  5330.3 1588.86  5443.0 1589.49  5467.2 1589.40  5517.7 1590.26  5523.9 1590.97
  5589.3 1591.77  5654.7 1593.68  5660.8 1594.52  5696.5 1596.06  5728.5 1596.70
#Mann=6,-1,0
  4597.5   0.035       0  4980.0   0.035       0  4991.2   0.035       0
  5013.5    0.07       0  5093.0   0.035       0  5443.0    0.07       0
Bank Sta=4980,4991.2
Exp/Cntr=0.3,0.1

Type RM Length L Ch R = 1,11892,544,544,544
BEGIN DESCRIPTION:
Mapping XS c7f072d5
END DESCRIPTION:
XS GIS Cut Line= 3
      1637080.33      6973304.57      1637189.69      6973040.71
      1637486.57      6972637.93
#Sta/Elev= 30
  4711.2 1593.33  4750.5 1593.31  4804.9 1593.81  4830.7 1593.42  4859.0 1593.13
  4924.3 1589.97  4934.8 1588.17  4942.8 1584.62  4948.2 1586.06  4966.7 1579.14
  4972.1 1580.31  4978.1 1577.73  5025.6 1577.62  5026.1 1577.12  5036.3 1577.12
  5036.8 1577.62  5045.8 1579.09  5052.0 1578.76  5060.4 1579.91  5066.6 1579.27
  5081.3 1580.61  5106.4 1581.27  5152.3 1581.99  5306.6 1586.19  5331.9 1587.73
  5352.8 1587.47  5402.9 1589.34  5423.7 1590.85  5438.4 1592.67  5497.2 1595.96
#Mann=7,-1,0
  4711.2    0.07       0  4750.5   0.035       0  4830.7    0.07       0
  5025.6    0.07       0  5036.8    0.07       0  5106.4   0.035       0
  5306.6    0.07       0
Bank Sta=5025.6,5036.8
Exp/Cntr=0.3,0.1

Type RM Length L Ch R = 1,11348,551,551,551
BEGIN DESCRIPTION:
Mapping XS 7ecabbf7
END DESCRIPTION:
XS GIS Cut Line= 3
      1637146.88      6973231.38      1637674.24      6973010.02
      1638031.78      6972854.57
#Sta/Elev= 30
  4425.8 1593.89  4449.2 1593.35  4472.9 1591.92  4527.0 1591.60  4532.2 1590.79
  4578.8 1589.95  4608.1 1588.42  4643.6 1587.78  4708.5 1585.44  4726.8 1584.25
  4732.3 1584.85  4738.3 1583.80  4761.4 1583.07  4832.7 1581.87  4861.9 1580.48
  5000.9 1577.00  5009.5 1576.63  5025.7 1574.36  5026.2 1573.86  5036.4 1573.86
  5036.9 1574.36  5051.1 1578.20  5062.0 1580.95  5114.4 1586.12  5143.3 1590.22
  5166.7 1594.83  5173.0 1596.78  5190.1 1598.57  5336.3 1603.35  5387.6 1604.02
#Mann=6,-1,0
  4425.8   0.035       0  4527.0    0.07       0  4643.6   0.035       0
  5025.7   0.035       0  5036.9   0.035       0  5051.1    0.07       0
Bank Sta=5025.7,5036.9
Exp/Cntr=0.3,0.1

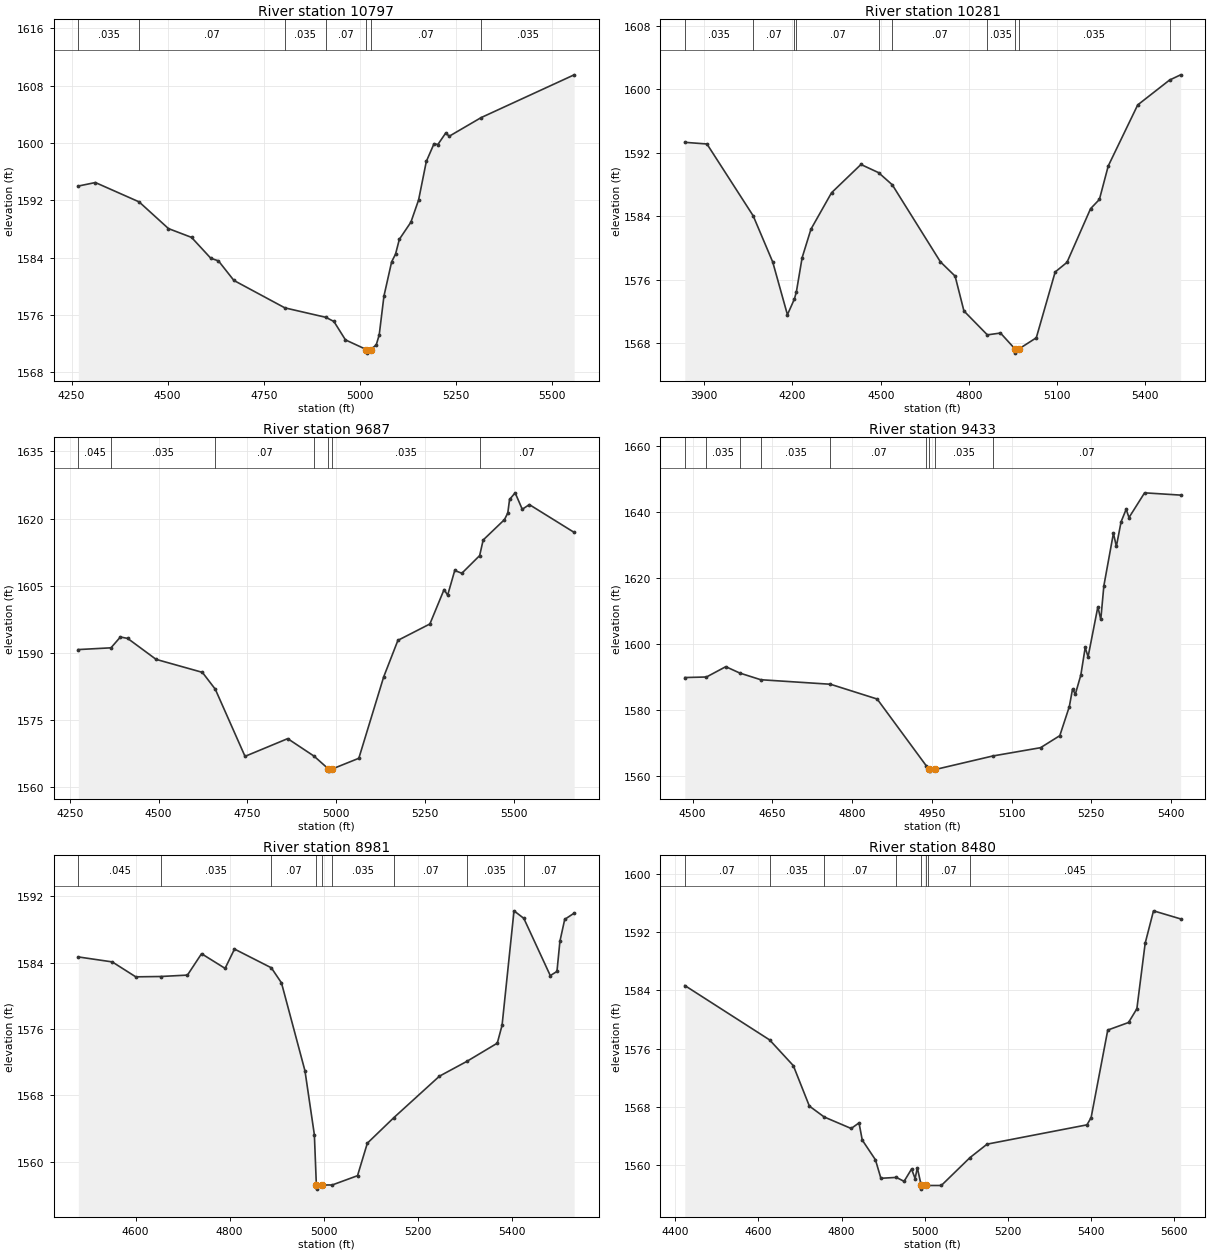
Type RM Length L Ch R = 1,10797,516,516,516
BEGIN DESCRIPTION:
Mapping XS 82be0698
END DESCRIPTION:
XS GIS Cut Line= 3
      1636850.76      6973436.09      1637583.37      6973460.40
      1638138.97      6973488.18
#Sta/Elev= 30
  4267.7 1593.98  4312.0 1594.47  4425.7 1591.77  4502.1 1588.04  4562.1 1586.81
  4612.1 1583.90  4632.1 1583.53  4672.2 1580.80  4804.8 1576.97  4911.3 1575.65
  4932.3 1575.07  4962.3 1572.50  5016.7 1571.15  5017.2 1570.65  5028.1 1571.15
  5042.4 1571.81  5050.1 1573.20  5062.4 1578.62  5082.4 1583.40  5092.5 1584.47
  5102.5 1586.55  5132.5 1588.94  5152.5 1592.04  5172.6 1597.42  5192.6 1599.89
  5202.6 1599.78  5222.6 1601.35  5232.6 1600.95  5315.2 1603.54  5557.0 1609.51
#Mann=7,-1,0
  4267.7   0.035       0  4425.7    0.07       0  4804.8   0.035       0
  4911.3    0.07       0  5016.7    0.07       0  5028.1    0.07       0
  5315.2   0.035       0
Bank Sta=5016.7,5028.1
Exp/Cntr=0.3,0.1

Type RM Length L Ch R = 1,10281,594,594,594
BEGIN DESCRIPTION:
Mapping XS 03eff990
END DESCRIPTION:
XS GIS Cut Line= 3
      1636016.19      6973784.54      1637182.83      6973761.11
      1637700.55      6973794.93
#Sta/Elev= 30
  3834.0 1593.32  3909.3 1593.11  4066.4 1584.07  4132.9 1578.25  4182.9 1571.61
  4206.7 1573.59  4213.5 1574.52  4232.9 1578.79  4262.9 1582.38  4332.9 1586.97
  4432.9 1590.53  4492.8 1589.50  4539.4 1587.97  4703.0 1578.27  4753.0 1576.47
  4783.0 1572.08  4862.6 1569.07  4907.3 1569.30  4957.3 1567.27  4957.8 1566.77
  4968.7 1567.27  5029.0 1568.70  5093.2 1576.99  5133.3 1578.20  5213.5 1584.96
  5243.6 1586.13  5273.6 1590.34  5373.8 1598.03  5482.0 1601.16  5519.7 1601.82
#Mann=10,-1,0
  3834.0   0.035       0  4066.4    0.07       0  4206.7   0.035       0
  4213.5    0.07       0  4492.8   0.035       0  4539.4    0.07       0
  4862.6   0.035       0  4957.3    0.07       0  4968.7   0.035       0
  5482.0   0.035       0
Bank Sta=4957.3,4968.7
Exp/Cntr=0.3,0.1

Type RM Length L Ch R = 1,9687,254,254,254
BEGIN DESCRIPTION:
Mapping XS 07298a43
END DESCRIPTION:
XS GIS Cut Line= 3
      1635956.30      6973977.25      1636680.23      6974011.11
      1637351.10      6974013.71
#Sta/Elev= 30
  4273.9 1590.73  4365.8 1591.12  4392.3 1593.54  4412.8 1593.22  4492.8 1588.54
  4623.0 1585.64  4659.4 1581.87  4743.1 1566.87  4863.2 1570.83  4937.2 1566.93
  4977.7 1564.07  4978.2 1563.57  4989.1 1564.07  5063.4 1566.44  5133.4 1584.63
  5173.4 1592.79  5263.4 1596.45  5303.4 1604.15  5313.4 1602.88  5333.4 1608.40
  5353.4 1607.78  5403.5 1611.73  5413.4 1615.21  5473.4 1619.77  5482.7 1621.25
  5487.7 1624.27  5503.4 1625.75  5523.4 1622.08  5543.4 1623.12  5669.5 1616.91
#Mann=7,-1,0
  4273.9   0.045       0  4365.8   0.035       0  4659.4    0.07       0
  4937.2   0.035       0  4977.7   0.035       0  4989.1   0.035       0
  5403.5    0.07       0
Bank Sta=4977.7,4989.1
Exp/Cntr=0.3,0.1

Type RM Length L Ch R = 1,9433,452,452,452
BEGIN DESCRIPTION:
Mapping XS e3b8c73c
END DESCRIPTION:
XS GIS Cut Line= 3
      1636006.49      6974052.04      1636502.99      6974190.92
      1636888.44      6974350.66
#Sta/Elev= 30
  4485.2 1589.83  4526.0 1590.00  4562.3 1593.12  4588.8 1591.18  4628.1 1589.17
  4759.3 1587.80  4847.1 1583.33  4939.4 1563.15  4945.2 1562.02  4945.7 1561.52
  4956.6 1562.02  5064.6 1566.10  5154.5 1568.61  5190.7 1572.25  5208.6 1581.03
  5214.6 1586.31  5220.0 1584.83  5230.3 1590.62  5238.5 1598.92  5243.9 1596.09
  5262.3 1611.23  5267.8 1607.40  5273.6 1617.60  5291.6 1633.49  5297.1 1629.51
  5306.0 1636.95  5315.5 1640.72  5320.9 1638.23  5350.2 1645.71  5418.0 1645.02
#Mann=9,-1,0
  4485.2   0.045       0  4526.0   0.035       0  4588.8    0.07       0
  4628.1   0.035       0  4759.3    0.07       0  4939.4   0.035       0
  4945.2   0.035       0  4956.6   0.035       0  5064.6    0.07       0
Bank Sta=4945.2,4956.6
Exp/Cntr=0.3,0.1

Type RM Length L Ch R = 1,8981,501,501,501
BEGIN DESCRIPTION:
Mapping XS 1bc18885
END DESCRIPTION:
XS GIS Cut Line= 3
      1635832.86      6974597.17      1636353.68      6974583.29
      1636874.56      6974701.35
#Sta/Elev= 30
  4478.0 1584.70  4550.2 1584.10  4600.2 1582.30  4653.0 1582.34  4710.2 1582.51
  4740.2 1585.09  4790.3 1583.32  4810.3 1585.65  4888.7 1583.39  4910.3 1581.57
  4960.3 1570.96  4980.3 1563.25  4984.5 1557.20  4985.0 1556.70  4996.2 1557.20
  5018.2 1557.20  5072.1 1558.32  5093.0 1562.24  5149.6 1565.33  5246.4 1570.32
  5304.6 1572.10  5369.5 1574.30  5379.7 1576.46  5405.1 1590.26  5426.0 1589.35
  5482.3 1582.45  5496.5 1582.95  5502.8 1586.59  5513.0 1589.23  5533.1 1589.98
#Mann=9,-1,0
  4478.0   0.045       0  4653.0   0.035       0  4888.7    0.07       0
  4984.5    0.07       0  4996.2    0.07       0  5018.2   0.035       0
  5149.6    0.07       0  5304.6   0.035       0  5426.0    0.07       0
Bank Sta=4984.5,4996.2
Exp/Cntr=0.3,0.1

Type RM Length L Ch R = 1,8480,447,447,447
BEGIN DESCRIPTION:
Mapping XS 0855b6fc
END DESCRIPTION:
XS GIS Cut Line= 3
      1635857.12      6974888.83      1636405.77      6975069.40
      1637020.13      6975086.75
#Sta/Elev= 30
  4423.2 1584.67  4627.1 1577.20  4684.2 1573.66  4722.7 1568.11  4758.4 1566.61
  4823.3 1565.03  4842.1 1565.80  4849.9 1563.44  4881.6 1560.73  4894.7 1558.19
  4931.8 1558.31  4950.5 1557.77  4968.4 1559.46  4977.0 1558.15  4982.3 1559.64
  4991.7 1557.20  4992.2 1556.70  5003.8 1557.20  5009.0 1557.20  5040.0 1557.20
  5108.7 1561.02  5150.1 1562.88  5390.2 1565.53  5400.2 1566.53  5440.2 1578.55
  5490.2 1579.59  5510.2 1581.48  5530.2 1590.49  5550.2 1594.93  5615.4 1593.82
#Mann=8,-1,0
  4423.2    0.07       0  4627.1   0.035       0  4758.4    0.07       0
  4931.8   0.035       0  4991.7   0.035       0  5003.8   0.035       0
  5009.0    0.07       0  5108.7   0.045       0
Bank Sta=4991.7,5003.8
Exp/Cntr=0.3,0.1

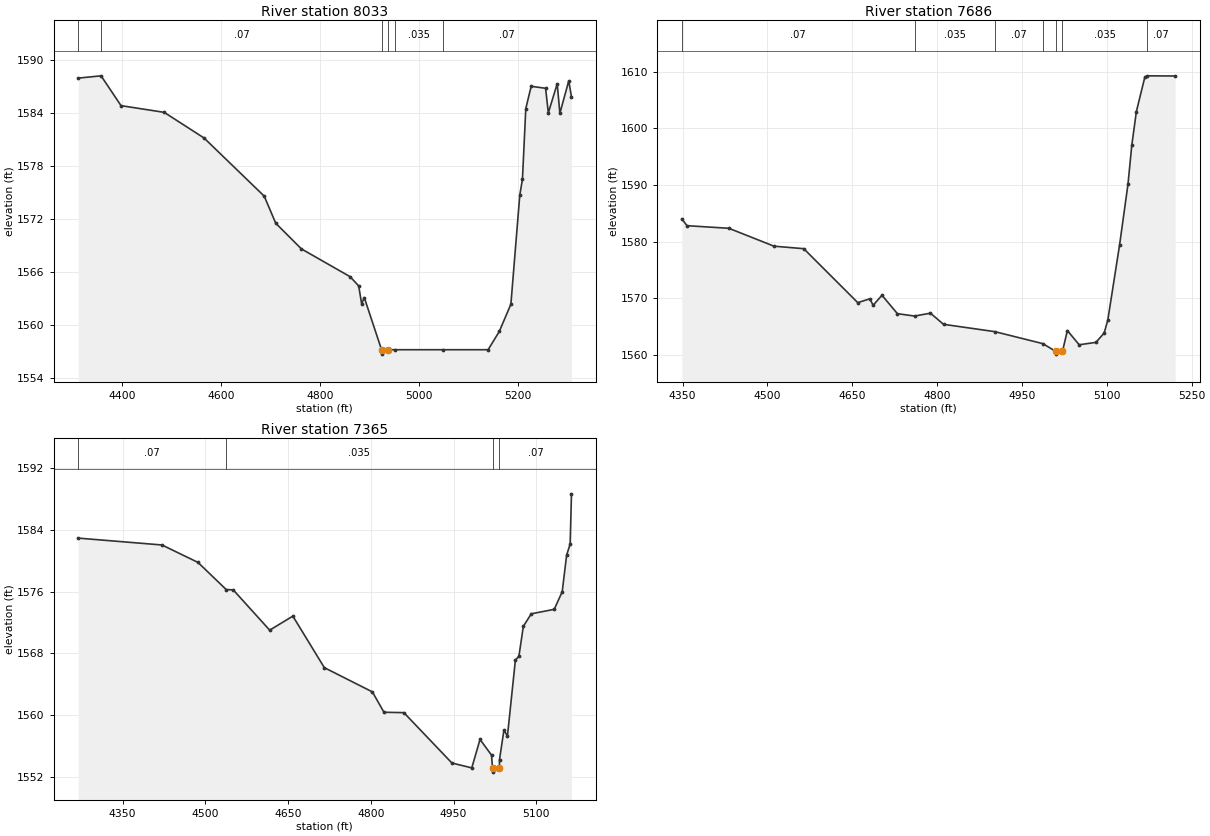
Type RM Length L Ch R = 1,8033,347,347,347
BEGIN DESCRIPTION:
Mapping XS c59e07b8
END DESCRIPTION:
XS GIS Cut Line= 3
      1635725.74      6975220.25      1636357.25      6975500.20
      1636639.78      6975623.13
#Sta/Elev= 30
  4310.4 1587.99  4356.7 1588.25  4397.1 1584.87  4484.5 1584.11  4565.3 1581.20
  4687.1 1574.61  4710.4 1571.54  4762.4 1568.63  4861.0 1565.48  4878.4 1564.43
  4884.3 1562.43  4889.8 1563.10  4924.7 1557.20  4925.2 1556.70  4937.0 1557.20
  4952.7 1557.20  5049.3 1557.20  5140.5 1557.20  5163.2 1559.28  5186.6 1562.36
  5204.6 1574.71  5210.0 1576.53  5216.8 1584.54  5227.7 1587.06  5256.9 1586.84
  5262.4 1584.05  5280.4 1587.35  5285.8 1584.00  5303.8 1587.68  5309.3 1585.86
#Mann=6,-1,0
  4310.4   0.035       0  4356.7    0.07       0  4924.7   0.035       0
  4937.0    0.07       0  4952.7   0.035       0  5049.3    0.07       0
Bank Sta=4924.7,4937
Exp/Cntr=0.3,0.1

Type RM Length L Ch R = 1,7686,321,321,321
BEGIN DESCRIPTION:
Mapping XS c5f2b834
END DESCRIPTION:
XS GIS Cut Line= 3
      1635647.59      6975461.12      1636205.34      6975793.17
      1636387.66      6975921.22
#Sta/Elev= 30
  4348.8 1584.01  4357.9 1582.82  4431.9 1582.36  4511.7 1579.20  4564.3 1578.76
  4659.7 1569.24  4681.1 1569.91  4686.9 1568.77  4702.5 1570.54  4729.8 1567.29
  4760.1 1566.87  4788.2 1567.38  4811.3 1565.41  4901.9 1564.12  4986.9 1562.00
  5009.3 1560.65  5009.8 1560.15  5021.6 1560.65  5030.2 1564.31  5051.1 1561.80
  5080.8 1562.23  5095.3 1563.89  5101.7 1566.17  5122.6 1579.49  5137.4 1590.19
  5144.1 1597.03  5152.2 1602.97  5167.0 1608.99  5171.7 1609.27  5220.7 1609.24
#Mann=7,-1,0
  4348.8    0.07       0  4760.1   0.035       0  4901.9    0.07       0
  4986.9   0.035       0  5009.3   0.035       0  5021.6   0.035       0
  5171.7    0.07       0
Bank Sta=5009.3,5021.6
Exp/Cntr=0.3,0.1

Type RM Length L Ch R = 1,7365,302,302,302
BEGIN DESCRIPTION:
Mapping XS a2e97e13
END DESCRIPTION:
XS GIS Cut Line= 3
      1635504.38      6975678.15      1636112.02      6976083.97
      1636240.07      6976185.97
#Sta/Elev= 30
  4269.4 1582.93  4421.3 1582.04  4486.6 1579.78  4537.8 1576.26  4550.5 1576.22
  4616.6 1571.00  4658.6 1572.82  4715.7 1566.14  4802.8 1563.00  4823.8 1560.36
  4859.9 1560.31  4947.0 1553.78  4983.0 1553.15  4998.0 1556.84  5018.8 1554.80
  5020.7 1553.10  5021.2 1552.60  5033.1 1553.10  5033.3 1554.23  5041.3 1558.04
  5047.7 1557.29  5062.1 1567.12  5068.5 1567.62  5076.5 1571.49  5090.9 1573.12
  5132.5 1573.70  5147.0 1575.98  5155.0 1580.72  5161.4 1582.17  5163.8 1588.67
#Mann=4,-1,0
  4269.4    0.07       0  4537.8   0.035       0  5020.7   0.035       0
  5033.1    0.07       0
Bank Sta=5020.7,5033.1
Exp/Cntr=0.3,0.1