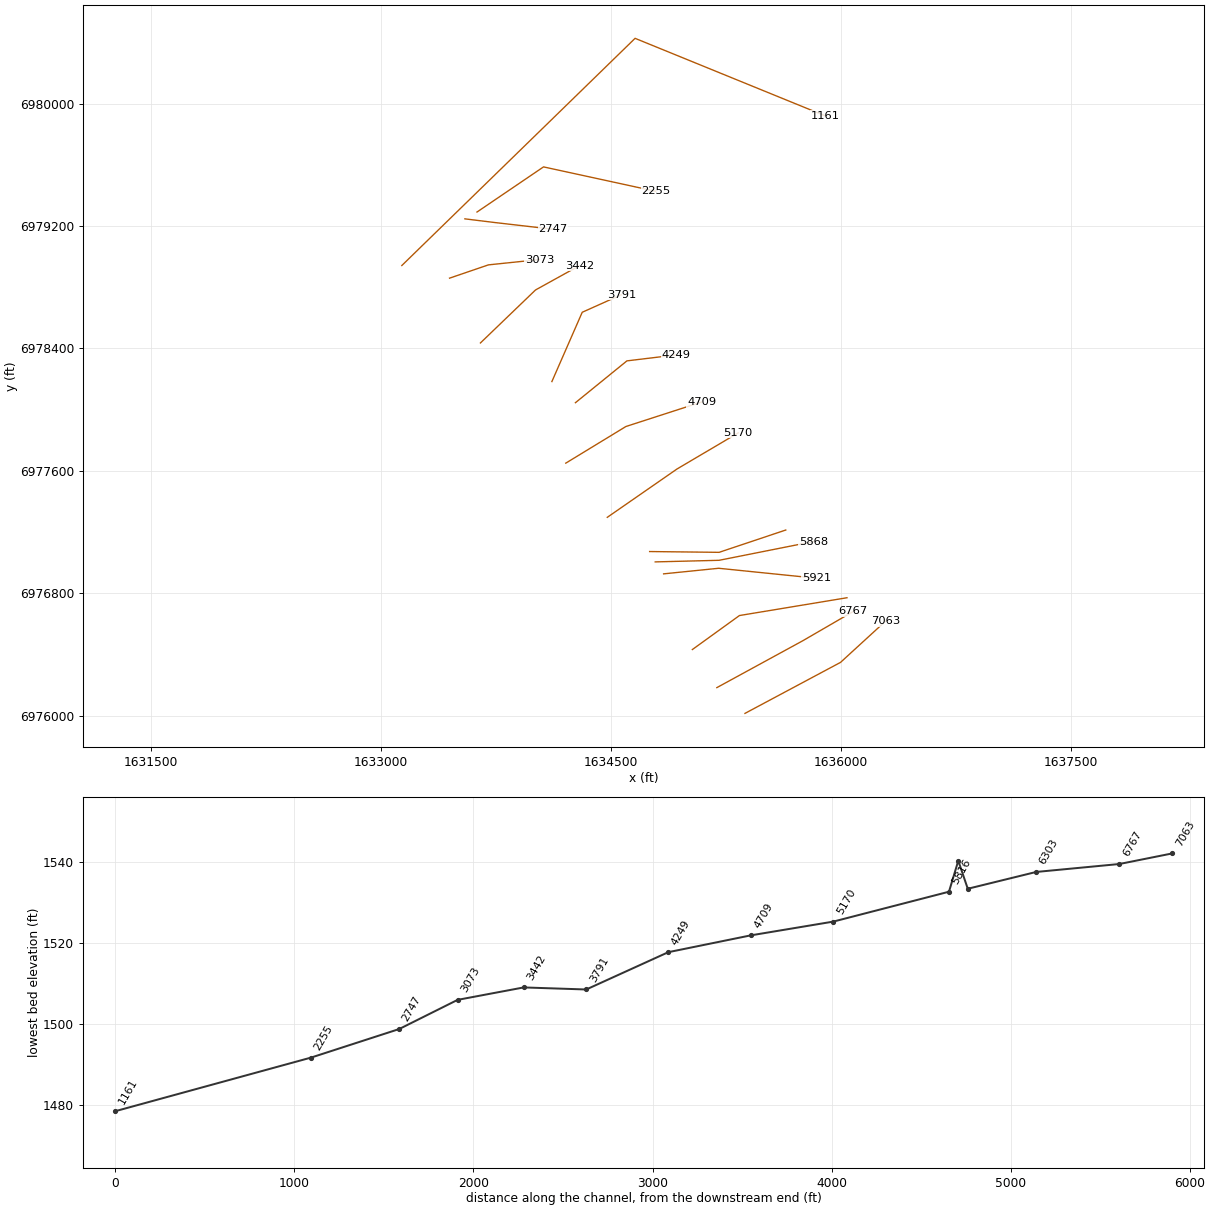
HEC-RAS study Hog Creek.prj: Hog Creek Base Level Engineering

--- Hog Creek.g01 (geometry) --- (continued)

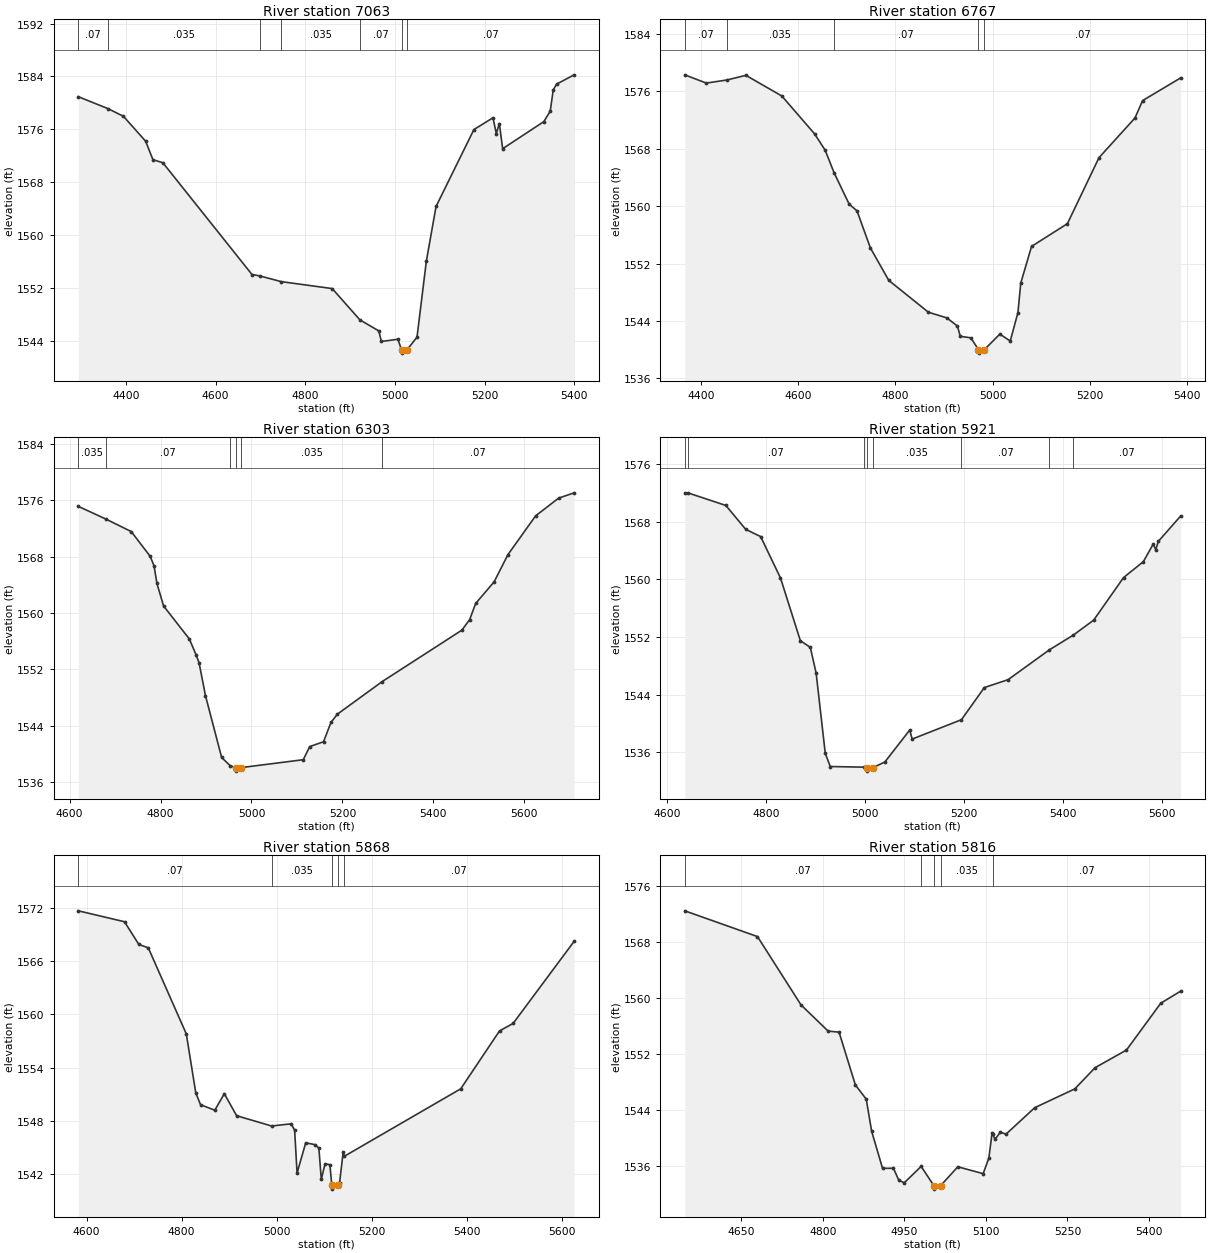
Type RM Length L Ch R = 1,7063,296,296,296
BEGIN DESCRIPTION:
Mapping XS 823ccf8a
END DESCRIPTION:
XS GIS Cut Line= 3
      1635373.37      6976014.36      1635996.66      6976347.71
      1636290.91      6976617.73
#Sta/Elev= 30
  4293.7 1580.94  4360.3 1579.12  4394.4 1577.97  4443.9 1574.20  4460.2 1571.40
  4482.2 1570.95  4681.1 1554.03  4698.2 1553.82  4746.5 1552.95  4860.1 1551.90
  4921.8 1547.17  4964.1 1545.49  4969.8 1543.89  5006.7 1544.23  5014.7 1542.63
  5015.2 1542.13  5027.1 1542.63  5049.3 1544.55  5070.2 1556.08  5091.8 1564.33
  5176.3 1575.97  5218.8 1577.75  5226.2 1575.36  5233.0 1576.88  5240.4 1573.07
  5332.3 1577.17  5346.5 1578.75  5353.2 1581.94  5360.6 1582.84  5399.9 1584.25
#Mann=7,-1,0
  4293.7    0.07       0  4360.3   0.035       0  4698.2    0.07       0
  4746.5   0.035       0  4921.8    0.07       0  5014.7    0.07       0
  5027.1    0.07       0
Bank Sta=5014.7,5027.1
Exp/Cntr=0.3,0.1

Type RM Length L Ch R = 1,6767,464,464,464
BEGIN DESCRIPTION:
Mapping XS 5092a93e
END DESCRIPTION:
XS GIS Cut Line= 3
      1635189.78      6976182.65      1635748.78      6976488.19
      1636080.22      6976680.81
#Sta/Elev= 30
  4366.6 1578.31  4410.7 1577.16  4452.5 1577.58  4492.3 1578.24  4566.3 1575.36
  4633.7 1570.08  4655.5 1567.80  4673.9 1564.65  4704.8 1560.29  4721.0 1559.34
  4748.6 1554.17  4786.4 1549.65  4868.0 1545.21  4906.0 1544.42  4927.8 1543.27
  4933.5 1541.86  4955.3 1541.64  4970.9 1540.01  4971.4 1539.51  4983.3 1540.01
  5014.9 1542.16  5036.4 1541.20  5052.2 1545.17  5058.0 1549.27  5080.2 1554.39
  5154.0 1557.56  5219.0 1566.76  5293.0 1572.29  5308.8 1574.72  5387.0 1577.88
#Mann=5,-1,0
  4366.6    0.07       0  4452.5   0.035       0  4673.9    0.07       0
  4970.9    0.07       0  4983.3    0.07       0
Bank Sta=4970.9,4983.3
Exp/Cntr=0.3,0.1

Type RM Length L Ch R = 1,6303,382,382,382
BEGIN DESCRIPTION:
Mapping XS 14f93024
END DESCRIPTION:
XS GIS Cut Line= 3
      1635029.97      6976431.72      1635337.28      6976653.96
      1636038.65      6976770.28
#Sta/Elev= 30
  4619.3 1575.12  4680.1 1573.31  4735.7 1571.54  4777.4 1568.02  4785.9 1566.65
  4792.1 1564.18  4806.8 1560.98  4863.3 1556.31  4878.0 1554.09  4884.7 1552.94
  4898.9 1548.25  4934.4 1539.49  4953.0 1538.33  4964.9 1538.05  4965.4 1537.55
  4977.3 1538.05  5113.9 1539.17  5128.0 1541.03  5158.4 1541.72  5174.8 1544.46
  5188.8 1545.63  5287.5 1550.26  5462.5 1557.55  5479.7 1559.04  5492.9 1561.34
  5533.5 1564.41  5563.9 1568.27  5624.7 1573.77  5675.4 1576.29  5709.5 1577.04
#Mann=6,-1,0
  4619.3   0.035       0  4680.1    0.07       0  4953.0   0.035       0
  4964.9   0.035       0  4977.3   0.035       0  5287.5    0.07       0
Bank Sta=4964.9,4977.3
Exp/Cntr=0.3,0.1

Type RM Length L Ch R = 1,5921,53,53,53
BEGIN DESCRIPTION:
Mapping XS 375e0289
END DESCRIPTION:
XS GIS Cut Line= 3
      1634842.45      6976926.53      1635201.87      6976962.99
      1635839.89      6976897.88
#Sta/Elev= 30
  4635.6 1572.03  4642.5 1572.01  4718.6 1570.28  4758.8 1566.96  4788.9 1565.96
  4829.1 1560.21  4869.3 1551.50  4889.4 1550.58  4901.2 1547.00  4919.6 1535.89
  4929.7 1534.04  4998.1 1533.95  5003.8 1533.90  5004.3 1533.40  5016.4 1533.90
  5040.2 1534.67  5090.4 1539.10  5095.4 1537.85  5195.0 1540.54  5241.3 1545.00
  5289.4 1546.10  5372.9 1550.24  5421.2 1552.28  5462.4 1554.36  5522.7 1560.26
  5562.9 1562.48  5582.9 1564.93  5587.9 1564.12  5593.1 1565.29  5638.2 1568.81
#Mann=8,-1,0
  4635.6   0.035       0  4642.5    0.07       0  4998.1   0.035       0
  5003.8   0.035       0  5016.4   0.035       0  5195.0    0.07       0
  5372.9   0.035       0  5421.2    0.07       0
Bank Sta=5003.8,5016.4
Exp/Cntr=0.3,0.1

Type RM Length L Ch R = 1,5868,52,52,52
BEGIN DESCRIPTION:
Mapping XS 96fa9034
END DESCRIPTION:
XS GIS Cut Line= 3
      1634787.85      6977004.66      1635204.47      6977015.07
      1635819.06      6977137.47
#Sta/Elev= 30
  4582.7 1571.67  4679.9 1570.44  4709.9 1567.89  4729.9 1567.50  4809.9 1557.81
  4829.9 1551.15  4839.9 1549.83  4869.9 1549.21  4889.9 1551.07  4915.8 1548.59
  4989.5 1547.43  5030.6 1547.68  5037.9 1546.95  5043.0 1542.13  5061.2 1545.54
  5081.6 1545.32  5088.9 1544.92  5094.0 1541.42  5101.9 1543.18  5112.1 1543.07
  5116.0 1540.82  5116.5 1540.32  5128.6 1540.82  5132.5 1541.06  5140.0 1544.48
  5142.4 1544.02  5387.4 1551.62  5469.0 1558.14  5497.7 1558.99  5626.1 1568.24
#Mann=5,-1,0
  4582.7    0.07       0  4989.5   0.035       0  5116.0   0.035       0
  5128.6   0.035       0  5142.4    0.07       0
Bank Sta=5116,5128.6
Exp/Cntr=0.3,0.1

Type RM Length L Ch R = 1,5816,646,646,646
BEGIN DESCRIPTION:
Mapping XS 21bbdabb
END DESCRIPTION:
XS GIS Cut Line= 3
      1634751.30      6977072.36      1635204.47      6977067.15
      1635639.37      6977212.99
#Sta/Elev= 30
  4546.2 1572.41  4679.9 1568.73  4759.9 1558.98  4809.9 1555.23  4829.9 1555.09
  4859.9 1547.55  4879.9 1545.52  4889.9 1540.91  4909.9 1535.64  4929.9 1535.65
  4939.9 1533.92  4949.9 1533.58  4980.9 1535.92  5004.2 1533.17  5004.7 1532.67
  5016.8 1533.17  5048.3 1535.86  5094.9 1534.88  5105.4 1537.09  5111.4 1540.75
  5112.8 1540.49  5116.7 1539.78  5126.5 1540.79  5137.1 1540.53  5189.8 1544.30
  5263.6 1546.99  5300.7 1550.01  5358.5 1552.53  5421.6 1559.22  5458.1 1560.94
#Mann=5,-1,0
  4546.2    0.07       0  4980.9   0.035       0  5004.2   0.035       0
  5016.8   0.035       0  5112.8    0.07       0
Bank Sta=5004.2,5016.8
Exp/Cntr=0.3,0.1

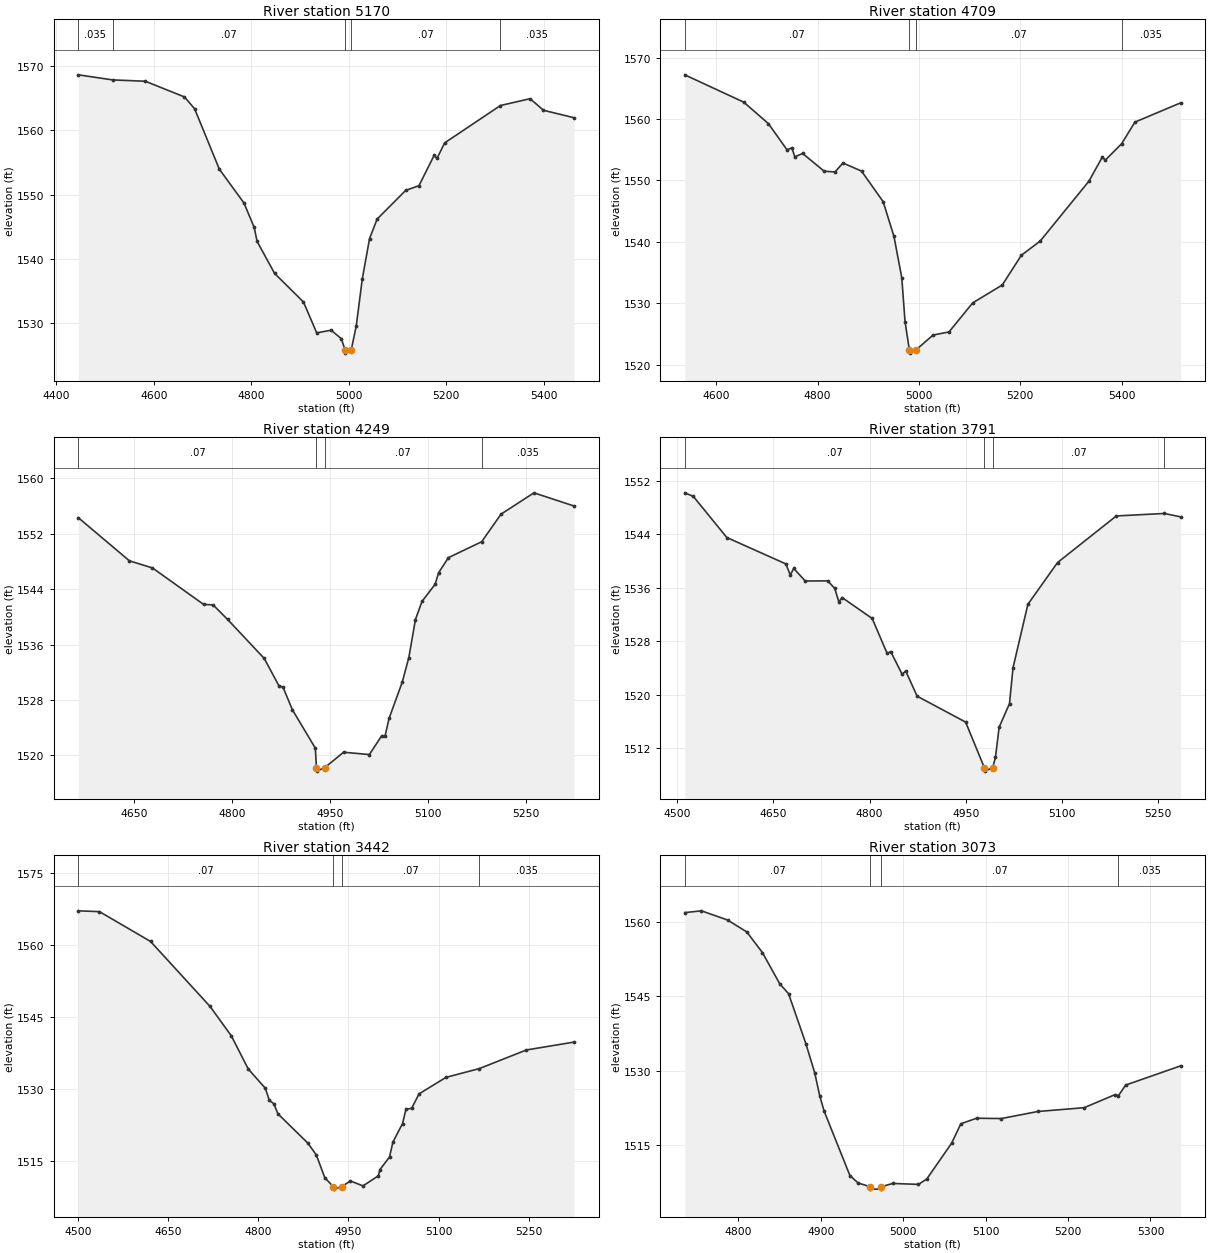
Type RM Length L Ch R = 1,5170,461,461,461
BEGIN DESCRIPTION:
Mapping XS 800e4d04
END DESCRIPTION:
XS GIS Cut Line= 3
      1634475.02      6977296.05      1634929.91      6977612.03
      1635329.25      6977848.17
#Sta/Elev= 30
  4445.0 1568.65  4515.2 1567.86  4582.4 1567.65  4662.8 1565.21  4683.7 1563.36
  4734.4 1553.96  4785.0 1548.68  4806.0 1544.88  4812.0 1542.69  4847.8 1537.72
  4907.2 1533.25  4934.3 1528.45  4964.0 1528.86  4984.9 1527.54  4992.5 1525.79
  4993.0 1525.29  5005.2 1525.79  5015.5 1529.53  5028.0 1536.90  5042.8 1543.14
  5058.4 1546.18  5116.9 1550.64  5144.2 1551.38  5175.4 1556.11  5181.2 1555.62
  5196.9 1558.04  5311.5 1563.87  5372.4 1564.93  5399.8 1563.13  5462.8 1561.96
#Mann=5,-1,0
  4445.0   0.035       0  4515.2    0.07       0  4992.5    0.07       0
  5005.2    0.07       0  5311.5   0.035       0
Bank Sta=4992.5,5005.2
Exp/Cntr=0.3,0.1

Type RM Length L Ch R = 1,4709,460,460,460
BEGIN DESCRIPTION:
Mapping XS 8a98112a
END DESCRIPTION:
XS GIS Cut Line= 3
      1634204.23      6977650.24      1634596.57      6977889.81
      1635089.64      6978049.54
#Sta/Elev= 30
  4538.1 1567.19  4654.4 1562.74  4703.0 1559.25  4739.7 1554.99  4749.3 1555.30
  4755.1 1553.84  4770.6 1554.39  4813.2 1551.49  4834.5 1551.39  4850.0 1552.84
  4886.7 1551.52  4929.3 1546.55  4950.7 1540.88  4966.1 1534.15  4972.5 1527.03
  4981.1 1522.39  4981.6 1521.89  4993.8 1522.39  5027.7 1524.83  5059.2 1525.34
  5106.0 1530.07  5164.3 1532.98  5202.0 1537.82  5239.2 1540.14  5335.2 1549.88
  5361.9 1553.84  5367.2 1553.28  5399.8 1555.98  5425.9 1559.49  5516.1 1562.63
#Mann=4,-1,0
  4538.1    0.07       0  4981.1    0.07       0  4993.8    0.07       0
  5399.8   0.035       0
Bank Sta=4981.1,4993.8
Exp/Cntr=0.3,0.1

Type RM Length L Ch R = 1,4249,458,458,458
BEGIN DESCRIPTION:
Mapping XS 3f07bd74
END DESCRIPTION:
XS GIS Cut Line= 3
      1634267.12      6978045.39      1634603.08      6978318.85
      1634926.04      6978357.92
#Sta/Elev= 30
  4564.6 1554.32  4642.8 1548.09  4678.0 1547.07  4756.3 1541.80  4770.7 1541.74
  4793.0 1539.63  4849.0 1534.00  4871.3 1530.09  4877.7 1529.86  4892.1 1526.59
  4927.2 1521.05  4928.8 1518.24  4929.3 1517.74  4941.5 1518.24  4970.4 1520.47
  5009.8 1520.13  5028.6 1522.83  5033.7 1522.77  5040.0 1525.36  5060.2 1530.61
  5070.2 1534.14  5080.3 1539.62  5090.4 1542.25  5110.5 1544.72  5115.6 1546.35
  5130.7 1548.55  5181.6 1550.85  5211.2 1554.83  5261.6 1557.91  5323.1 1556.00
#Mann=4,-1,0
  4564.6    0.07       0  4928.8    0.07       0  4941.5    0.07       0
  5181.6   0.035       0
Bank Sta=4928.8,4941.5
Exp/Cntr=0.3,0.1

Type RM Length L Ch R = 1,3791,349,349,349
BEGIN DESCRIPTION:
Mapping XS 85ffcf0f
END DESCRIPTION:
XS GIS Cut Line= 3
      1634113.50      6978183.43      1634311.42      6978636.56
      1634566.61      6978751.13
#Sta/Elev= 30
  4511.5 1550.19  4524.8 1549.66  4577.1 1543.50  4669.3 1539.55  4676.2 1537.90
  4681.6 1538.87  4699.6 1536.99  4734.7 1537.01  4745.7 1535.88  4751.9 1533.89
  4757.3 1534.50  4804.1 1531.38  4827.5 1526.14  4833.0 1526.43  4850.9 1523.02
  4856.4 1523.53  4874.3 1519.75  4950.0 1515.87  4979.3 1509.03  4979.8 1508.53
  4992.2 1509.03  4996.6 1510.61  5002.3 1515.10  5018.5 1518.64  5024.0 1524.00
  5047.2 1533.50  5093.5 1539.75  5185.3 1546.73  5260.4 1547.10  5285.7 1546.59
#Mann=4,-1,0
  4511.5    0.07       0  4979.3    0.07       0  4992.2    0.07       0
  5260.4   0.035       0
Bank Sta=4979.3,4992.2
Exp/Cntr=0.3,0.1

Type RM Length L Ch R = 1,3442,369,369,369
BEGIN DESCRIPTION:
Mapping XS f1bc1a8c
END DESCRIPTION:
XS GIS Cut Line= 3
      1633647.32      6978436.00      1634006.73      6978782.39
      1634291.60      6978940.36
#Sta/Elev= 30
  4500.7 1567.08  4535.9 1566.91  4620.8 1560.70  4719.7 1547.16  4755.1 1541.04
  4783.4 1534.09  4811.7 1530.10  4818.6 1527.53  4825.8 1526.87  4832.8 1524.74
  4882.4 1518.66  4896.6 1516.17  4910.7 1511.44  4924.9 1509.54  4925.4 1509.04
  4938.7 1509.54  4953.2 1510.74  4974.3 1509.72  4999.9 1511.82  5002.4 1513.10
  5018.4 1515.74  5024.1 1518.86  5040.1 1522.72  5045.8 1525.72  5055.1 1525.87
  5067.6 1528.91  5112.2 1532.34  5168.1 1534.19  5246.1 1538.06  5325.6 1539.71
#Mann=4,-1,0
  4500.7    0.07       0  4924.9    0.07       0  4938.7    0.07       0
  5168.1   0.035       0
Bank Sta=4924.9,4938.7
Exp/Cntr=0.3,0.1

Type RM Length L Ch R = 1,3073,326,326,326
BEGIN DESCRIPTION:
Mapping XS cb278e0c
END DESCRIPTION:
XS GIS Cut Line= 3
      1633445.93      6978859.63      1633699.44      6978946.45
      1634031.38      6978981.03
#Sta/Elev= 30
  4734.9 1561.99  4755.1 1562.35  4786.8 1560.49  4810.1 1558.08  4829.1 1553.89
  4850.2 1547.55  4860.8 1545.57  4881.9 1535.41  4892.5 1529.57  4898.7 1524.84
  4904.0 1521.77  4935.3 1508.71  4945.3 1507.21  4959.6 1506.47  4960.1 1505.97
  4973.0 1505.97  4973.5 1506.47  4987.3 1507.12  5018.5 1506.93  5028.6 1508.03
  5058.7 1515.28  5069.9 1519.21  5088.9 1520.33  5119.1 1520.27  5163.4 1521.70
  5219.6 1522.47  5256.9 1525.11  5261.2 1524.92  5269.9 1527.05  5336.6 1530.94
#Mann=4,-1,0
  4734.9    0.07       0  4959.6    0.07       0  4973.5    0.07       0
  5261.2   0.035       0
Bank Sta=4959.6,4973.5
Exp/Cntr=0.3,0.1

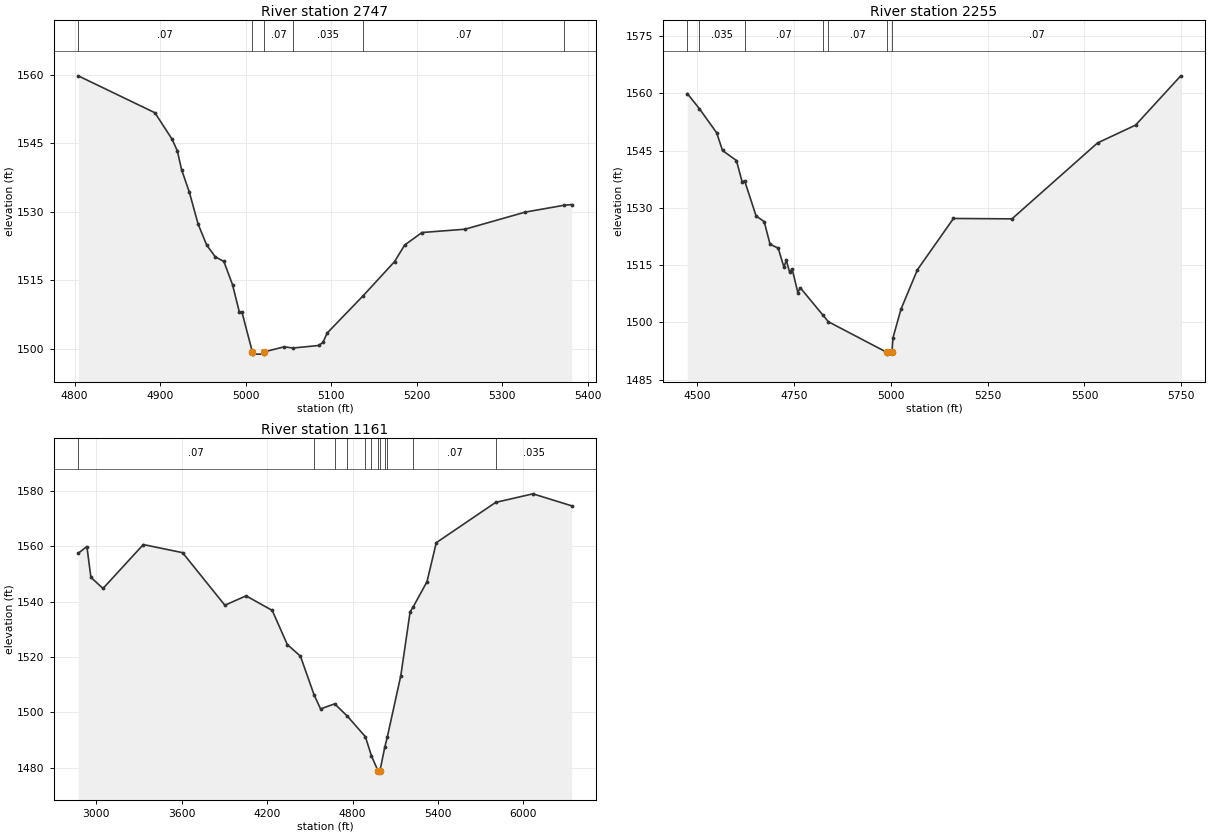
Type RM Length L Ch R = 1,2747,492,492,492
BEGIN DESCRIPTION:
Mapping XS fb2b07df
END DESCRIPTION:
XS GIS Cut Line= 3
      1633545.98      6979247.30      1633736.07      6979223.86
      1634118.89      6979179.59
#Sta/Elev= 30
  4804.2 1559.73  4893.9 1551.64  4914.0 1545.83  4920.1 1543.28  4925.1 1539.15
  4934.2 1534.20  4944.3 1527.31  4954.4 1522.65  4964.4 1520.10  4974.5 1519.06
  4984.6 1513.99  4992.7 1507.91  4995.7 1507.91  5007.8 1499.27  5008.3 1498.77
  5021.2 1498.77  5021.7 1499.27  5045.0 1500.37  5055.3 1500.11  5085.3 1500.66
  5090.3 1501.34  5095.3 1503.40  5137.2 1511.53  5174.1 1519.05  5185.9 1522.67
  5206.1 1525.41  5256.4 1526.13  5326.9 1529.88  5372.3 1531.38  5381.1 1531.52
#Mann=6,-1,0
  4804.2    0.07       0  5007.8    0.07       0  5021.7    0.07       0
  5055.3   0.035       0  5137.2    0.07       0  5372.3   0.035       0
Bank Sta=5007.8,5021.7
Exp/Cntr=0.3,0.1

Type RM Length L Ch R = 1,2255,1094,1094,1094
BEGIN DESCRIPTION:
Mapping XS 782a55ac
END DESCRIPTION:
XS GIS Cut Line= 3
      1633624.96      6979291.85      1634059.02      6979587.01
      1634790.82      6979427.47
#Sta/Elev= 30
  4474.6 1559.91  4505.7 1555.96  4550.5 1549.63  4565.5 1545.01  4601.4 1542.39
  4616.3 1536.74  4622.5 1537.11  4652.2 1527.88  4673.2 1526.38  4688.2 1520.47
  4709.2 1519.46  4724.1 1514.47  4730.1 1516.27  4739.0 1513.09  4745.1 1514.04
  4760.0 1507.84  4766.1 1509.11  4823.9 1502.03  4838.8 1500.20  4989.0 1492.22
  4989.5 1491.72  5002.9 1492.22  5005.6 1496.01  5026.1 1503.44  5068.7 1513.81
  5161.7 1527.22  5312.7 1527.12  5533.7 1546.99  5631.9 1551.65  5748.5 1564.55
#Mann=7,-1,0
  4474.6    0.07       0  4505.7   0.035       0  4622.5    0.07       0
  4823.9   0.035       0  4838.8    0.07       0  4989.0    0.07       0
  5002.9    0.07       0
Bank Sta=4989,5002.9
Exp/Cntr=0.3,0.1

Type RM Length L Ch R = 1,1161,0,0,0
BEGIN DESCRIPTION:
Mapping XS 61e2ce17
END DESCRIPTION:
XS GIS Cut Line= 3
      1633134.56      6978942.25      1634656.31      6980427.46
      1635895.03      6979921.41
#Sta/Elev= 30
  2873.6 1557.41  2934.5 1559.84  2962.8 1548.71  3047.7 1544.72  3330.6 1560.55
  3606.3 1557.63  3903.4 1538.66  4051.8 1542.06  4235.7 1536.80  4341.7 1524.49
  4433.7 1520.31  4530.1 1506.29  4575.2 1501.27  4674.2 1503.10  4762.8 1498.68
  4889.7 1491.26  4932.4 1484.36  4978.2 1478.97  4978.7 1478.47  4992.2 1478.97
  5025.9 1487.42  5043.6 1491.09  5138.8 1513.32  5203.8 1536.26  5225.8 1538.09
  5322.6 1547.18  5387.5 1561.22  5804.6 1575.76  6066.0 1578.85  6338.1 1574.53
#Mann=12,-1,0
  2873.6    0.07       0  4530.1   0.035       0  4674.2    0.07       0
  4762.8    0.16       0  4889.7    0.07       0  4932.4    0.16       0
  4978.2    0.07       0  4992.2    0.16       0  5025.9    0.07       0
  5043.6    0.16       0  5225.8    0.07       0  5804.6   0.035       0
Bank Sta=4978.2,4992.2
Exp/Cntr=0.3,0.1

Chan Stop Cuts=-1