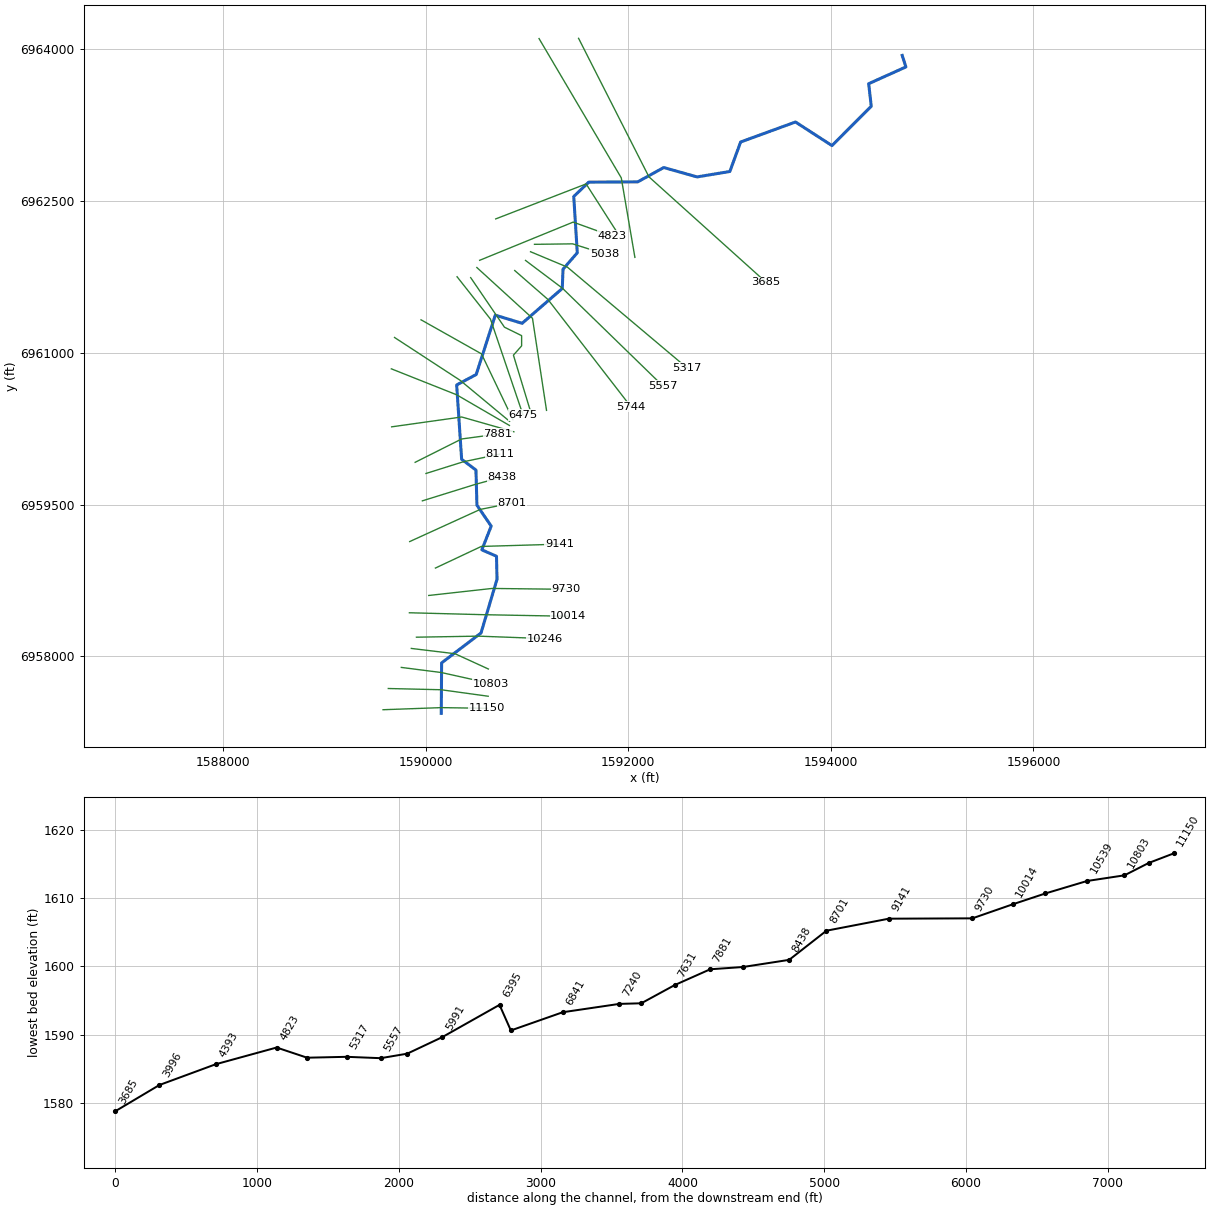
--- Mesquite Creek.prj (project) ---

Proj Title=Mesquite Creek Base Level Engineering
Current Plan=p01
Default Exp/Contr=0.3,0.1
English Units
Geom File=g01
Flow File=f01
Plan File=p01
Y Axis Title=Elevation
X Axis Title(PF)=Main Channel Distance
X Axis Title(XS)=Station
BEGIN DESCRIPTION:
Mesquite Creek
END DESCRIPTION:
DSS Export Rating Curves= 0
DSS Export Rating Curve Sorted= 0
DSS Export Volume Flow Curves= 0
DXF OffsetX= 0
DXF OffsetY= 0
DXF ScaleX= 1
DXF ScaleY= 10

--- Mesquite Creek.p01 (plan) ---

Plan Title=Multiple Run
Short Identifier=Multiple
Geom File=g01
Flow File=f01
Subcritical Flow
K Sum by GR= 0
Std Step Tol= 0.01
Critical Tol= 0.01
Num of Std Step Trials= 20
Max Error Tol= 0.3
Flow Tol Ratio= 0.001
Split Flow NTrial= 30
Split Flow Tol= 0.02
Split Flow Ratio= 0.02
Log Output Level= 0
Friction Slope Method= 1
Unsteady Friction Slope Method= 2
Unsteady Bridges Friction Slope Method= 1
Parabolic Critical Depth
Global Vel Dist=  1 , 1 , 1
Global Log Level= 0
CheckData=True
Encroach Param= -1, 0, 0, 0
BEGIN DESCRIPTION:
Multiple Run
END DESCRIPTION:

--- Mesquite Creek.f01 (steady flow) ---

Flow Title=Multiple
Number of Profiles=7
Profile Names=10-year,25-year,50-year,1pct_min,100-year,1pct_plu,500-year
River Rch & RM= Mesquite Creek,Reach-1,11150
     272     380     470     290     579    1155     887
River Rch & RM= Mesquite Creek,Reach-1,10014
     375     528     657     407     812    1619    1254
Boundary for River Rch & Prof#=Mesquite Creek,Reach-1,1
Up Type=0
Dn Type=3
Dn Slope=0.005
Boundary for River Rch & Prof#=Mesquite Creek,Reach-1,2
Up Type=0
Dn Type=3
Dn Slope=0.005
Boundary for River Rch & Prof#=Mesquite Creek,Reach-1,3
Up Type=0
Dn Type=3
Dn Slope=0.005
Boundary for River Rch & Prof#=Mesquite Creek,Reach-1,4
Up Type=0
Dn Type=3
Dn Slope=0.005
Boundary for River Rch & Prof#=Mesquite Creek,Reach-1,5
Up Type=0
Dn Type=3
Dn Slope=0.005
Boundary for River Rch & Prof#=Mesquite Creek,Reach-1,6
Up Type=0
Dn Type=3
Dn Slope=0.005
Boundary for River Rch & Prof#=Mesquite Creek,Reach-1,7
Up Type=0
Dn Type=3
Dn Slope=0.005

--- Mesquite Creek.g01 (geometry) ---

Geom Title=Existing Conditions
Program Version=4.10

River Reach=Mesquite Creek  ,Reach-1
Reach XY= 30
        1590155.        6957438.      1590158.45      6957936.75
      1590547.19      6958231.79       1590705.4        6958763.
      1590700.12      6958990.26      1590555.54      6959053.59
      1590647.91        6959288.      1590507.24      6959493.93
      1590497.28      6959841.66      1590355.99      6959948.28
      1590306.97      6960682.35      1590499.65      6960785.27
      1590688.29       6961371.8      1590953.28      6961291.34
      1591349.54      6961635.53      1591356.92      6961826.05
      1591497.67       6961987.9      1591462.81      6962544.19
      1591610.85      6962685.94      1592094.31      6962688.77
      1592351.35      6962830.27        1592680.       6962737.6
      1593003.75      6962791.45      1593110.18      6963082.59
      1593651.78      6963280.12      1594011.73      6963047.11
       1594399.6      6963435.57      1594374.23      6963658.57
      1594741.72      6963824.19        1594705.        6963938.

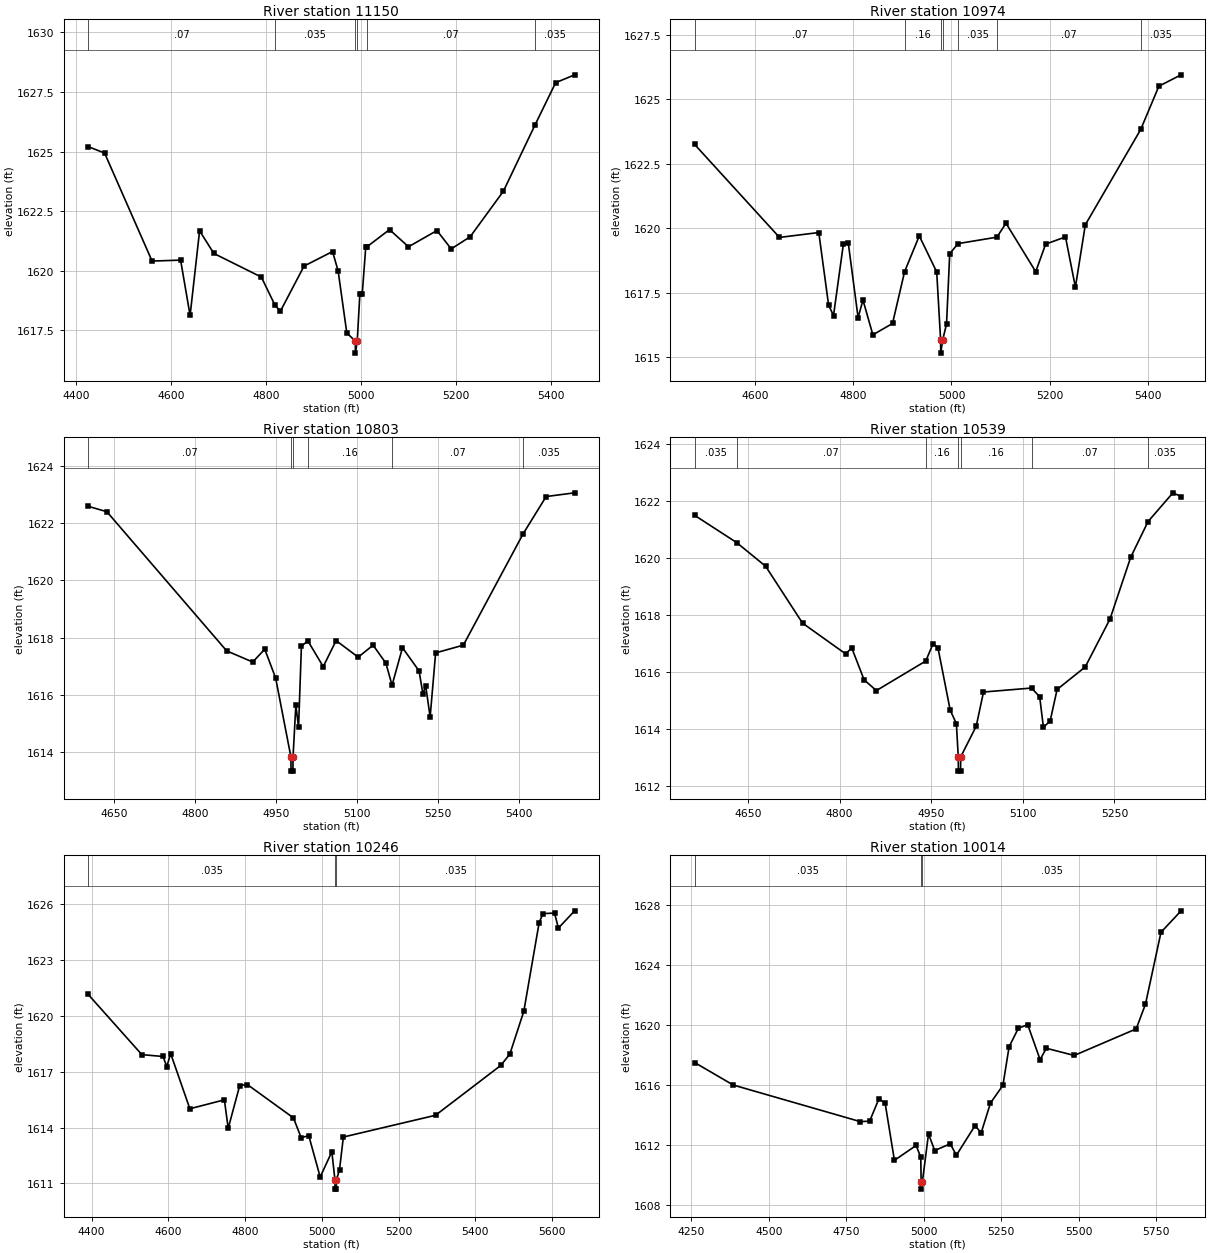
Type RM Length L Ch R = 1 ,11150   ,176,176,176
BEGIN DESCRIPTION:
Mesquite Creek 8.0
END DESCRIPTION:
XS GIS Cut Line= 3
      1589580.27      6957474.03        1590155.      6957494.86
      1590605.04        6957488.
#Sta/Elev= 30
  4424.9 1625.21  4459.6 1624.94  4559.7 1620.41  4619.8 1620.45  4639.8 1618.13
  4659.8 1621.68  4689.8 1620.73  4789.9 1619.74  4818.2 1618.58  4829.9  1618.3
  4879.9  1620.2    4940 1620.81  4951.8 1619.99    4970  1617.4    4988 1617.05
  4988.2 1616.55    4992 1617.05  4997.5 1619.02  5002.5 1619.02    5010 1621.01
  5013.3 1621.02    5060 1621.73    5100 1621.01    5160 1621.69    5190 1620.92
    5230 1621.43    5300 1623.34  5366.2  1626.1  5410.1 1627.89  5450.1 1628.22
#Mann= 6 ,-1 , 0
  4424.9     .07       0  4818.2    .035       0    4988    .035       0
    4992    .035       0  5013.3     .07       0  5366.2    .035       0
Bank Sta=4988,4992
XS Rating Curve= 0 ,0
Exp/Cntr=0.3,0.1

Type RM Length L Ch R = 1 ,10974   ,171,171,171
BEGIN DESCRIPTION:
Mapping XS ca9432b8
END DESCRIPTION:
XS GIS Cut Line= 3
      1589632.14      6957683.66      1590152.95      6957671.51
      1590618.19      6957607.28
#Sta/Elev= 30
    4477 1623.25  4649.9 1619.64  4729.9 1619.83  4749.9 1617.01  4759.9 1616.61
  4779.9 1619.37  4789.9 1619.43  4809.9 1616.53  4819.9 1617.21    4840 1615.86
    4880  1616.3  4904.6 1618.31  4934.5  1619.7    4970  1618.3    4978 1615.65
  4978.2 1615.15    4982 1615.65    4990 1616.28  4996.5 1619.01  5013.5  1619.4
  5092.5 1619.65  5111.1 1620.19  5171.6 1618.31  5191.8 1619.38  5232.2 1619.66
  5252.4 1617.71  5272.6 1620.13  5385.4 1623.83  5422.4 1625.51  5467.6 1625.95
#Mann= 7 ,-1 , 0
    4477     .07       0  4904.6     .16       0    4978     .07       0
    4982     .16       0  5013.5    .035       0  5092.5     .07       0
  5385.4    .035       0
Bank Sta=4978,4982
XS Rating Curve= 0 ,0
Exp/Cntr=0.3,0.1

Type RM Length L Ch R = 1 ,10803   ,264,264,264
BEGIN DESCRIPTION:
Mapping XS 8cb1f0e8
END DESCRIPTION:
XS GIS Cut Line= 3
       1589760.6        6957892.      1590154.68      6957841.65
      1590646.15      6957732.63
#Sta/Elev= 30
  4602.5 1622.59  4637.2  1622.4    4859 1617.54  4907.3 1617.15  4929.5  1617.6
  4949.7 1616.59  4977.9 1613.84  4978.2 1613.34  4981.7 1613.34  4981.9 1613.84
  4987.1 1615.65  4992.1 1614.87  4997.4  1617.7  5009.3 1617.89  5037.8 1616.99
  5061.6  1617.9  5102.5 1617.32  5130.1 1617.74  5153.8 1617.11  5165.2 1616.34
  5184.5 1617.65  5215.2 1616.84  5222.4 1616.03  5227.5 1616.32  5235.7 1615.23
  5245.9 1617.47  5297.2 1617.74  5407.9 1621.63  5450.5 1622.93  5503.2 1623.06
#Mann= 6 ,-1 , 0
  4602.5     .07       0  4977.9     .07       0  4981.9     .07       0
  5009.3     .16       0  5165.2     .07       0  5407.9    .035       0
Bank Sta=4977.9,4981.9
XS Rating Curve= 0 ,0
Exp/Cntr=0.3,0.1

Type RM Length L Ch R = 1 ,10539   ,293,293,293
BEGIN DESCRIPTION:
Mapping XS d2fa86c2
END DESCRIPTION:
XS GIS Cut Line= 3
      1589859.52       6958079.5       1590290.1      6958027.41
      1590619.95      6957876.38
#Sta/Elev= 30
  4562.7  1621.5  4631.7 1620.54    4679 1619.71  4739.5 1617.71    4810 1616.63
    4820 1616.84  4840.2 1615.72  4860.3 1615.34  4941.2 1616.38    4953 1616.98
  4961.1 1616.85  4981.2 1614.65  4991.3 1614.18  4994.4 1613.01  4994.6 1612.51
  4998.1 1612.51  4998.4 1613.01  5023.8 1614.09  5035.7 1615.29  5114.5 1615.43
  5127.7 1615.12  5133.8 1614.05  5144.8 1614.27  5156.2 1615.38  5202.2 1616.17
  5242.7 1617.85  5276.8 1620.03  5305.1 1621.28  5345.8 1622.29  5359.2 1622.16
#Mann= 7 ,-1 , 0
  4562.7    .035       0  4631.7     .07       0  4941.2     .16       0
  4994.4     .07       0  4998.4     .16       0  5114.5     .07       0
  5305.1    .035       0
Bank Sta=4994.4,4998.4
XS Rating Curve= 0 ,0
Exp/Cntr=0.3,0.1

Type RM Length L Ch R = 1 ,10246   ,232,232,232
BEGIN DESCRIPTION:
Mapping XS 04d3d39d
END DESCRIPTION:
XS GIS Cut Line= 3
      1589909.93      6958190.61      1590519.27      6958201.02
       1591177.3      6958176.72
#Sta/Elev= 30
  4391.1 1621.16  4531.1 1617.92  4586.2 1617.82  4596.2 1617.28  4606.2 1617.98
  4656.2 1615.01  4746.2 1615.49  4756.2 1613.96  4786.2 1616.26  4806.2 1616.31
  4926.2 1614.52  4946.2 1613.46  4966.2 1613.56  4995.9 1611.34  5026.3  1612.7
  5034.3 1611.19  5034.5 1610.69    5038 1610.69  5038.3 1611.19  5046.3 1611.74
  5056.3 1613.49  5296.5 1614.66  5466.6 1617.34  5490.2 1617.95  5526.6 1620.25
  5566.6 1625.02  5576.6  1625.5  5606.7 1625.53  5616.7 1624.72    5659 1625.65
#Mann= 3 ,-1 , 0
  4391.1    .035       0  5034.3    .035       0  5038.3    .035       0
Bank Sta=5034.3,5038.3
XS Rating Curve= 0 ,0
Exp/Cntr=0.3,0.1

Type RM Length L Ch R = 1 ,10014   ,284,284,284
BEGIN DESCRIPTION:
Mapping XS d71282bf
END DESCRIPTION:
XS GIS Cut Line= 3
      1589840.44      6958431.93      1590576.56      6958412.83
      1591409.84      6958397.21
#Sta/Elev= 30
  4260.4 1617.53    4385 1616.03  4795.1 1613.59  4825.2 1613.62  4855.2 1615.11
  4875.2 1614.82  4905.2 1611.01  4975.2    1612  4990.2 1611.22  4991.4 1609.59
  4991.7 1609.09  4995.5 1609.59  5015.2 1612.77  5035.2 1611.66  5085.2 1612.11
  5105.2 1611.35  5165.2 1613.32  5185.2 1612.85  5215.2 1614.83  5255.3 1616.01
  5275.3 1618.58  5305.3 1619.82  5335.3 1620.05  5375.3 1617.72  5395.3 1618.48
  5485.3    1618  5685.3 1619.77  5715.3 1621.42  5765.3 1626.21  5830.2 1627.64
#Mann= 3 ,-1 , 0
  4260.4    .035       0  4991.4    .035       0  4995.5    .035       0
Bank Sta=4991.4,4995.5
XS Rating Curve= 0 ,0
Exp/Cntr=0.3,0.1

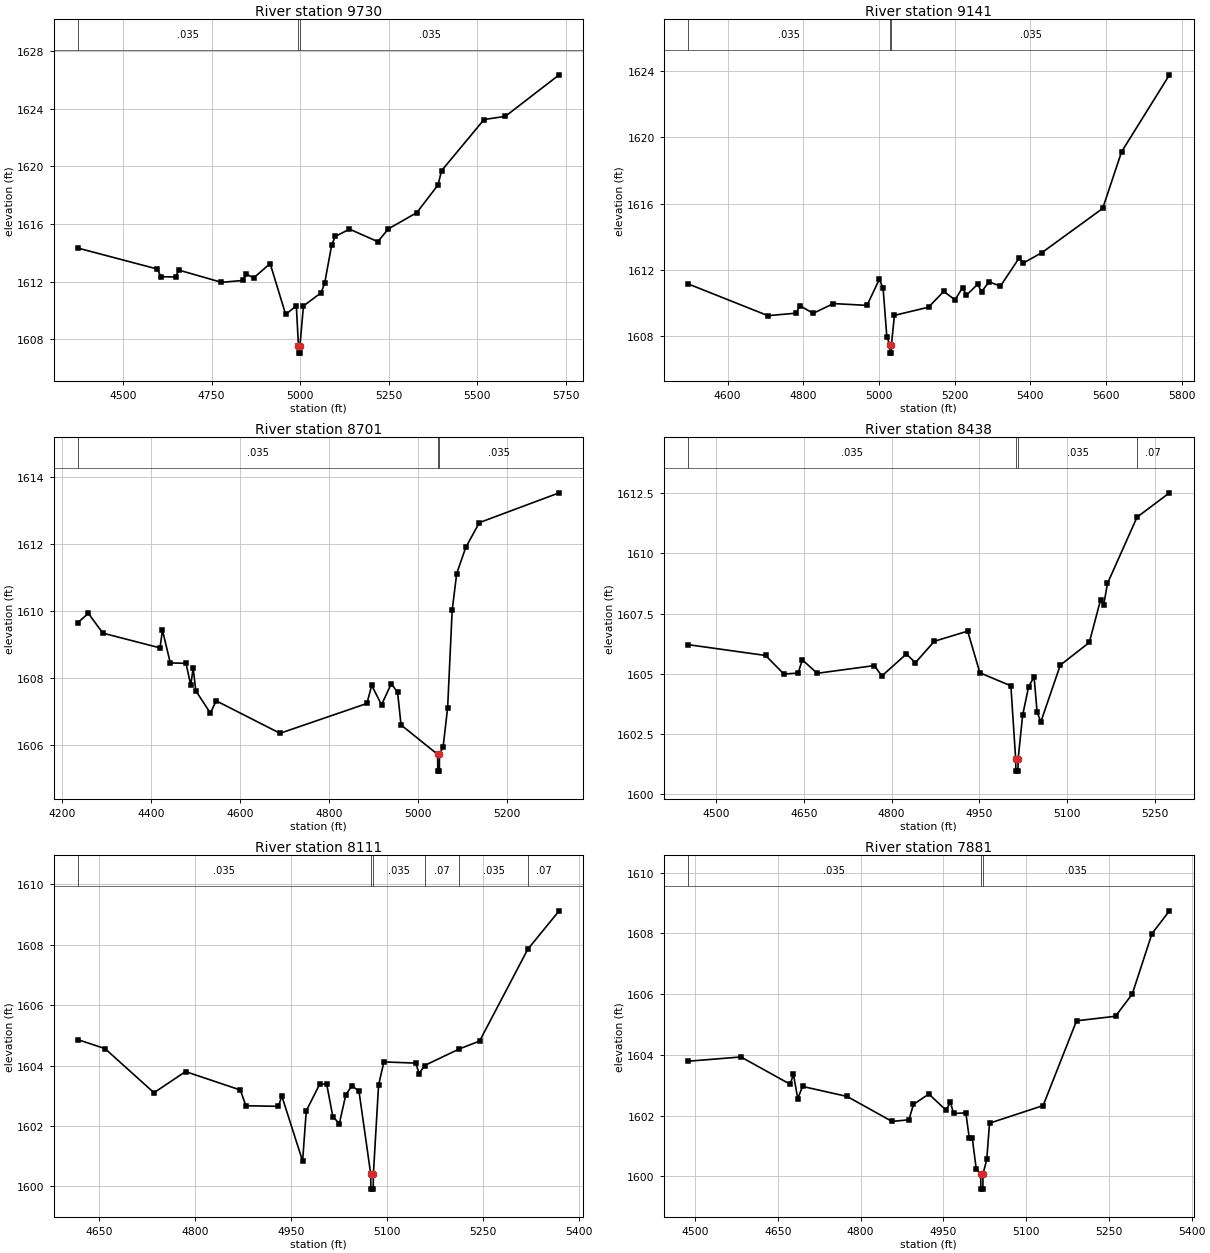
Type RM Length L Ch R = 1 ,9730    ,589,589,589
BEGIN DESCRIPTION:
Mapping XS 0cda41b9
END DESCRIPTION:
XS GIS Cut Line= 3
      1590031.17      6958602.79      1590656.19      6958672.23
      1591387.07      6958663.55
#Sta/Elev= 30
  4371.7 1614.33  4596.9 1612.87    4607 1612.34  4648.8 1612.32  4657.3  1612.8
    4778 1611.95  4838.4 1612.08  4848.4 1612.53  4868.6 1612.25  4915.4 1613.25
  4959.1 1609.73  4989.3 1610.31  4995.4 1607.54  4995.7 1607.04  4999.3 1607.04
  4999.5 1607.54  5009.4 1610.31  5059.4 1611.23  5069.4  1611.9  5089.4 1614.57
  5099.4 1615.13  5139.4 1615.64  5219.4 1614.77  5249.4 1615.66  5329.4 1616.78
  5389.4  1618.7  5399.4 1619.69  5519.4 1623.24  5579.4 1623.46  5731.5 1626.34
#Mann= 3 ,-1 , 0
  4371.7    .035       0  4995.4    .035       0  4999.5    .035       0
Bank Sta=4995.4,4999.5
XS Rating Curve= 0 ,0
Exp/Cntr=0.3,0.1

Type RM Length L Ch R = 1 ,9141    ,440,440,440
BEGIN DESCRIPTION:
Mapping XS faac48d5
END DESCRIPTION:
XS GIS Cut Line= 3
      1590097.19      6958873.64      1590550.29      6959087.16
      1591321.47      6959109.69
#Sta/Elev= 30
  4495.1 1611.17  4706.5 1609.25  4780.4  1609.4  4791.2 1609.85  4825.9 1609.39
  4879.6 1609.98  4968.2 1609.87  5000.8 1611.44  5010.7 1610.92  5020.7 1607.97
  5028.7 1607.49  5028.9 1606.99  5032.5 1606.99  5032.8 1607.49  5040.7 1609.27
  5130.8 1609.76  5170.8 1610.71  5200.8 1610.21  5220.8 1610.94  5230.8 1610.48
  5260.8 1611.15  5270.8 1610.69  5290.8 1611.29  5320.8 1611.03  5370.9 1612.75
  5380.9 1612.42  5430.9 1613.06    5591 1615.72    5641 1619.14  5767.5 1623.78
#Mann= 3 ,-1 , 0
  4495.1    .035       0  5028.7    .035       0  5032.8    .035       0
Bank Sta=5028.7,5032.8
XS Rating Curve= 0 ,0
Exp/Cntr=0.3,0.1

Type RM Length L Ch R = 1 ,8701    ,263,263,263
BEGIN DESCRIPTION:
Mapping XS afdee4db
END DESCRIPTION:
XS GIS Cut Line= 3
      1589843.31      6959135.18      1590539.52       6959452.9
      1590850.97      6959515.19
#Sta/Elev= 30
  4234.9 1609.66    4259 1609.94  4291.7 1609.35  4420.2 1608.91  4425.7 1609.44
  4443.3 1608.46  4478.6 1608.45  4489.3  1607.8  4494.8 1608.31  4500.6 1607.63
  4533.5 1606.96  4546.4 1607.33  4690.1 1606.36  4885.4 1607.25  4896.3 1607.79
  4918.3 1607.21  4940.3 1607.84  4954.5 1607.58  4962.2 1606.61  5044.5 1605.73
  5044.8 1605.23  5048.4 1605.23  5048.7 1605.73  5056.8 1605.95    5067 1607.12
  5077.2 1610.03  5087.4 1611.13  5107.8 1611.91  5138.3 1612.65  5317.8 1613.54
#Mann= 3 ,-1 , 0
  4234.9    .035       0  5044.5    .035       0  5048.7    .035       0
Bank Sta=5044.5,5048.7
XS Rating Curve= 0 ,0
Exp/Cntr=0.3,0.1

Type RM Length L Ch R = 1 ,8438    ,327,327,327
BEGIN DESCRIPTION:
Mapping XS 23562193
END DESCRIPTION:
XS GIS Cut Line= 3
      1589968.33      6959537.54      1590491.35       6959700.3
      1590757.23      6959773.01
#Sta/Elev= 30
  4451.8 1606.21  4584.5 1605.76  4615.9 1604.99  4640.3 1605.03  4647.3 1605.58
  4672.8 1605.02  4770.4 1605.34  4783.4 1604.91  4825.3 1605.82  4840.7 1605.46
  4873.2 1606.35  4930.1 1606.77    4951 1605.04    5004  1604.5  5012.2 1601.46
  5012.5 1600.96  5016.1 1600.96  5016.4 1601.46  5024.1 1603.28  5034.4 1604.47
  5043.7 1604.87  5048.8 1603.42  5055.2    1603  5088.5 1605.36  5138.1  1606.3
  5157.5 1608.08  5162.7 1607.86  5169.2 1608.75  5219.7  1611.5  5275.2 1612.51
#Mann= 4 ,-1 , 0
  4451.8    .035       0  5012.2    .035       0  5016.4    .035       0
  5219.7     .07       0
Bank Sta=5012.2,5016.4
XS Rating Curve= 0 ,0
Exp/Cntr=0.3,0.1

Type RM Length L Ch R = 1 ,8111    ,230,230,230
BEGIN DESCRIPTION:
Mapping XS b8661595
END DESCRIPTION:
XS GIS Cut Line= 3
      1590004.11      6959807.93       1590370.9      6959922.96
      1590731.13      6959998.68
#Sta/Elev= 30
  4616.8 1604.86  4659.6 1604.56  4736.1  1603.1  4785.4  1603.8  4871.1 1603.19
  4879.7 1602.67  4930.7 1602.65  4935.9 1602.99  4968.4 1600.84  4974.1  1602.5
    4995 1603.38    5006 1603.39  5015.6 1602.31  5025.8 1602.08    5036 1603.04
  5045.6 1603.33  5056.5 1603.15  5074.8 1600.41  5075.1 1599.91  5078.7 1599.91
    5079 1600.41  5087.1 1603.35  5095.4 1604.12  5145.3 1604.08  5150.4 1603.73
  5158.9    1604  5213.3 1604.55    5245 1604.81  5320.3 1607.85  5369.3 1609.12
#Mann= 6 ,-1 , 0
  4616.8    .035       0  5074.8    .035       0    5079    .035       0
  5158.9     .07       0  5213.3    .035       0  5320.3     .07       0
Bank Sta=5074.8,5079
XS Rating Curve= 0 ,0
Exp/Cntr=0.3,0.1

Type RM Length L Ch R = 1 ,7881    ,250,250,250
BEGIN DESCRIPTION:
Mapping XS 85098d3b
END DESCRIPTION:
XS GIS Cut Line= 3
      1589897.19      6959918.34      1590355.71      6960148.65
       1590711.9      6960197.22
#Sta/Elev= 30
  4487.2 1603.79  4583.3 1603.93  4672.6 1603.03  4678.2 1603.37  4686.2 1602.56
  4694.9 1602.96  4775.7 1602.63  4856.8 1601.81  4887.6 1601.86  4895.9 1602.37
  4923.8 1602.71  4954.8 1602.18  4962.9 1602.44  4968.5 1602.07  4990.8 1602.09
  4997.1 1601.25  5002.5 1601.25  5009.7 1600.23  5017.7 1600.08    5018 1599.58
  5021.6 1599.58  5021.9 1600.08  5028.7 1600.56  5033.7 1601.75  5130.8 1602.33
  5191.4 1605.12    5262 1605.27  5292.3    1606  5328.1 1607.99  5359.8 1608.74
#Mann= 3 ,-1 , 0
  4487.2    .035       0  5017.7    .035       0  5021.9    .035       0
Bank Sta=5017.7,5021.9
XS Rating Curve= 0 ,0
Exp/Cntr=0.3,0.1

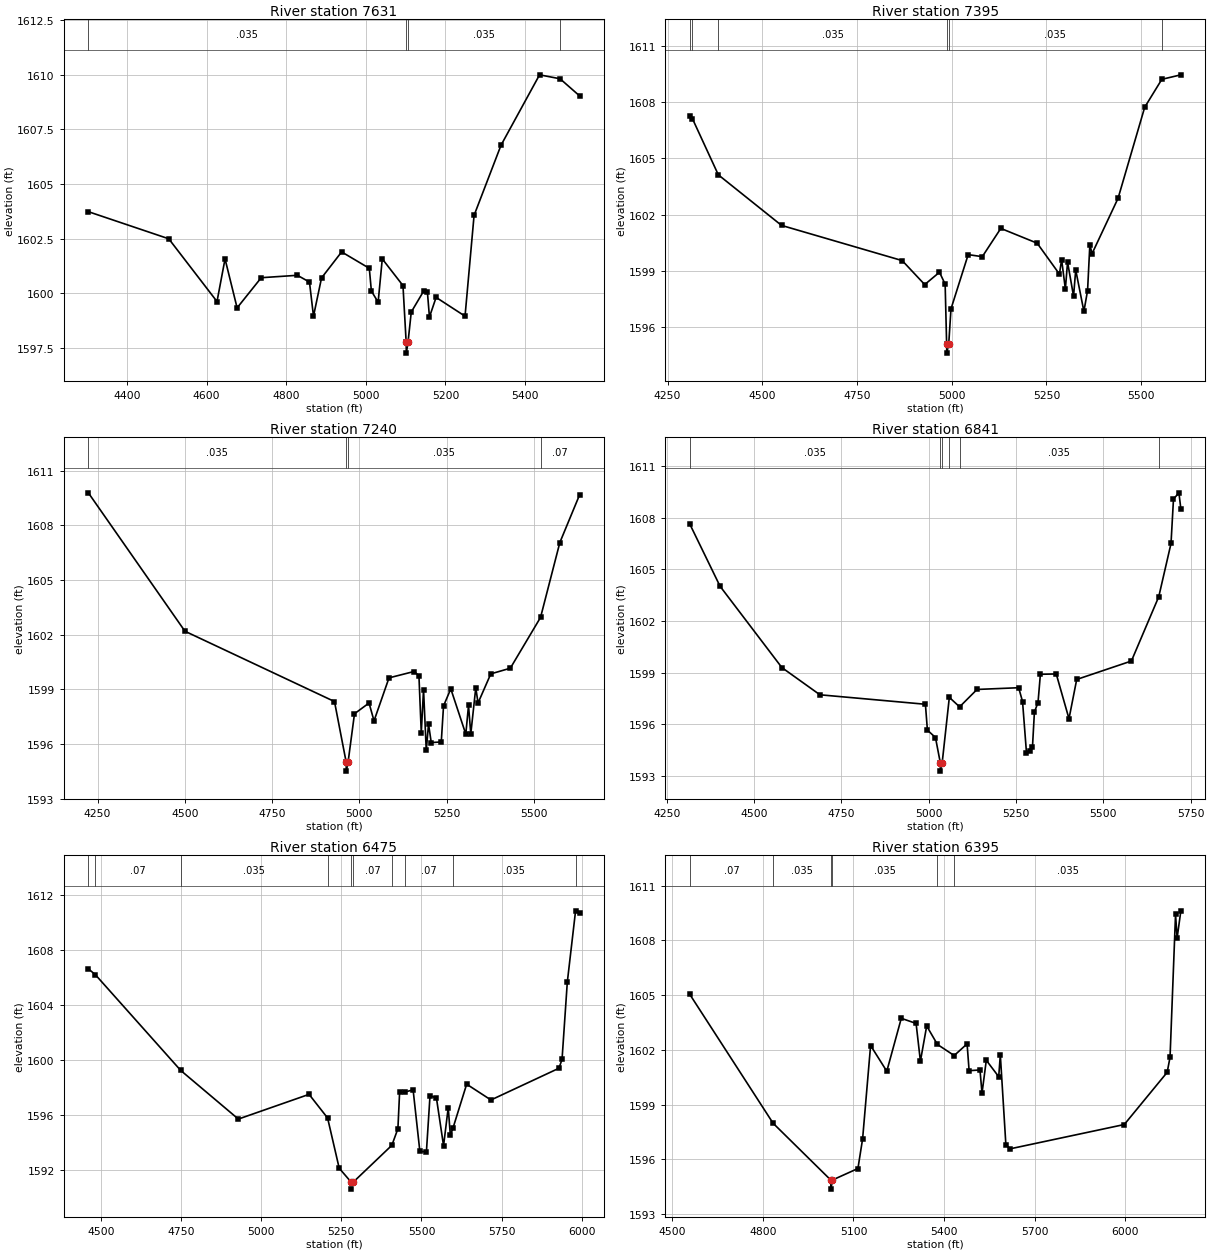
Type RM Length L Ch R = 1 ,7631    ,236,236,236
BEGIN DESCRIPTION:
Mapping XS 2135581d
END DESCRIPTION:
XS GIS Cut Line= 3
      1589664.93      6960268.66      1590356.58      6960366.03
      1590871.61      6960219.65
#Sta/Elev= 30
  4302.8 1603.74  4504.8  1602.5    4626 1599.63  4646.2 1601.58  4676.5 1599.34
  4737.1 1600.72    4828 1600.83  4858.3 1600.52  4868.4 1598.96  4888.6 1600.71
  4939.1  1601.9  5008.6 1601.15  5013.8 1600.11  5030.8  1599.6  5041.2 1601.58
  5093.2 1600.36  5101.2 1597.77  5101.6 1597.27  5105.9 1597.77    5114 1599.15
  5145.2 1600.11  5154.5 1600.08  5159.7 1598.92  5176.4 1599.82  5249.1 1598.96
  5271.8 1603.57  5339.5 1606.78  5436.3    1610  5487.8 1609.82  5536.7 1609.04
#Mann= 4 ,-1 , 0
  4302.8    .035       0  5101.2    .035       0  5105.9    .035       0
  5487.8     .07       0
Bank Sta=5101.2,5105.9
XS Rating Curve= 0 ,0
Exp/Cntr=0.3,0.1

Type RM Length L Ch R = 1 ,7395    ,155,155,155
BEGIN DESCRIPTION:
Mapping XS 67d1a3be
END DESCRIPTION:
XS GIS Cut Line= 3
      1589662.29      6960841.58      1590306.23      6960585.64
      1590827.82      6960282.35
#Sta/Elev= 30
  4308.5 1607.26  4315.7 1607.12  4384.1 1604.12  4550.9 1601.42  4869.4 1599.54
  4928.8 1598.26  4967.8 1598.92  4982.7 1598.28  4986.6  1595.1    4987  1594.6
  4992.2  1595.1  4998.1 1596.96  5043.5 1599.86  5080.7 1599.75  5129.6 1601.26
  5225.6 1600.47  5284.3 1598.82  5290.1 1599.59    5300 1598.02  5305.8 1599.46
  5321.6 1597.64  5327.3 1599.04  5348.9 1596.83  5358.6 1597.94  5364.6 1600.39
  5370.4 1599.91  5439.1 1602.87  5509.4 1607.73  5554.6 1609.22  5604.8 1609.46
#Mann= 6 ,-1 , 0
  4308.5    .035       0  4315.7     .07       0  4384.1    .035       0
  4986.6    .035       0  4992.2    .035       0  5554.6     .07       0
Bank Sta=4986.6,4992.2
XS Rating Curve= 0 ,0
Exp/Cntr=0.3,0.1

Type RM Length L Ch R = 1 ,7240    ,399,399,399
BEGIN DESCRIPTION:
Mapping XS 743c2fe3
END DESCRIPTION:
XS GIS Cut Line= 3
      1589693.59      6961151.45      1590341.82      6960728.01
        1590829.      6960323.33
#Sta/Elev= 30
  4223.5 1609.79  4500.4 1602.19  4928.9 1598.33  4962.3 1595.01  4962.7 1594.51
  4967.9 1595.01  4986.2 1597.66  5027.9 1598.25  5042.2 1597.27  5085.1 1599.63
  5156.8 1599.98  5170.9 1599.75  5177.6 1596.61  5184.1 1598.99  5191.9 1595.65
  5198.4 1597.09  5206.2 1596.08  5234.9 1596.11  5241.4 1598.09  5262.2 1599.03
  5305.2 1596.54    5313 1598.12  5319.5 1596.55  5333.8 1599.09  5340.3 1598.25
  5376.8 1599.85  5432.8 1600.16  5519.4 1602.95  5574.7 1607.06  5631.1 1609.67
#Mann= 4 ,-1 , 0
  4223.5    .035       0  4962.3    .035       0  4967.9    .035       0
  5519.4     .07       0
Bank Sta=4962.3,4967.9
XS Rating Curve= 0 ,0
Exp/Cntr=0.3,0.1

Type RM Length L Ch R = 1 ,6841    ,366,366,366
BEGIN DESCRIPTION:
Mapping XS f79b9173
END DESCRIPTION:
XS GIS Cut Line= 3
      1589955.07      6961326.08      1590551.89      6960989.69
      1590862.84      6960338.96
#Sta/Elev= 30
  4315.6 1607.64  4402.5 1604.02  4579.5  1599.3  4688.5 1597.72  4990.5 1597.17
  4996.2 1595.67  5019.3 1595.24    5033 1593.79  5033.5 1593.29  5038.6 1593.79
    5059 1597.57  5088.4 1597.02  5138.3 1598.03  5257.5 1598.13  5268.6 1597.33
  5279.9 1594.35  5290.7 1594.43    5297 1594.67  5302.6 1596.72  5312.9 1597.27
  5319.7 1598.91  5365.1 1598.93  5401.6 1596.33  5423.7 1598.61  5580.3 1599.68
  5658.6 1603.41  5693.7  1606.5  5700.8 1609.08  5716.4 1609.44  5721.9  1608.5
#Mann= 6 ,-1 , 0
  4315.6    .035       0    5033    .035       0  5038.6    .035       0
    5059     .07       0  5088.4    .035       0  5658.6     .07       0
Bank Sta=5033,5038.6
XS Rating Curve= 0 ,0
Exp/Cntr=0.3,0.1

Type RM Length L Ch R = 1 ,6475    ,80,80,80
BEGIN DESCRIPTION:
Mapping XS b60cdd82
END DESCRIPTION:
XS GIS Cut Line= 3
        1590311.      6961751.42      1590640.87      6961332.57
      1590962.06      6960386.35
#Sta/Elev= 30
  4460.6 1606.66  4482.9 1606.22  4748.8 1599.26  4928.6 1595.72  5149.2 1597.52
    5207  1595.8  5243.3 1592.14  5280.9 1591.12  5281.3 1590.62  5286.6 1591.12
  5407.5 1593.81  5426.4 1595.02  5431.7 1597.67  5447.3 1597.68  5473.8 1597.85
  5494.9 1593.37  5515.3 1593.33  5526.6 1597.43  5546.7 1597.24  5568.8 1593.78
  5583.4 1596.55    5590 1594.53  5597.9 1595.04  5640.9 1598.26  5716.7 1597.11
  5928.8 1599.42  5938.5 1600.07  5954.9 1605.69  5980.7 1610.88    5993 1610.74
#Mann= 10 ,-1 , 0
  4460.6    .035       0  4482.9     .07       0  4748.8    .035       0
    5207     .07       0  5280.9    .035       0  5286.6     .07       0
  5407.5    .035       0  5447.3     .07       0  5597.9    .035       0
  5980.7     .07       0
Bank Sta=5280.9,5286.6
XS Rating Curve= 0 ,0
Exp/Cntr=0.3,0.1

Type RM Length L Ch R = 1 ,6395    ,404,404,404
BEGIN DESCRIPTION:
Mapping XS b640bebf
END DESCRIPTION:
XS GIS Cut Line= 6
      1590445.47      6961742.63      1590778.78      6961253.08
      1590948.05      6961169.74      1590948.05      6961068.18
      1590867.32      6960977.04      1591044.39      6960393.75
#Sta/Elev= 30
  4557.9 1605.05    4834 1597.98  5024.8 1594.87  5025.2 1594.37  5030.5 1594.87
  5114.8  1595.5  5130.3 1597.13  5156.7 1602.24  5210.3 1600.83  5258.3 1603.73
  5307.3 1603.45  5321.6 1601.38  5342.4 1603.31  5377.8  1602.3  5433.4 1601.69
  5476.1 1602.33  5482.8 1600.86  5518.8  1600.9  5525.5 1599.63  5539.7 1601.43
  5580.8 1600.53  5586.1 1601.73  5604.5  1596.8    5619 1596.58  5996.4 1597.91
  6138.4 1600.77  6147.9  1601.6  6166.1 1609.43  6171.3 1608.13  6183.7 1609.62
#Mann= 6 ,-1 , 0
  4557.9     .07       0    4834    .035       0  5024.8    .035       0
  5030.5    .035       0  5377.8     .07       0  5433.4    .035       0
Bank Sta=5024.8,5030.5
XS Rating Curve= 0 ,0
Exp/Cntr=0.3,0.1

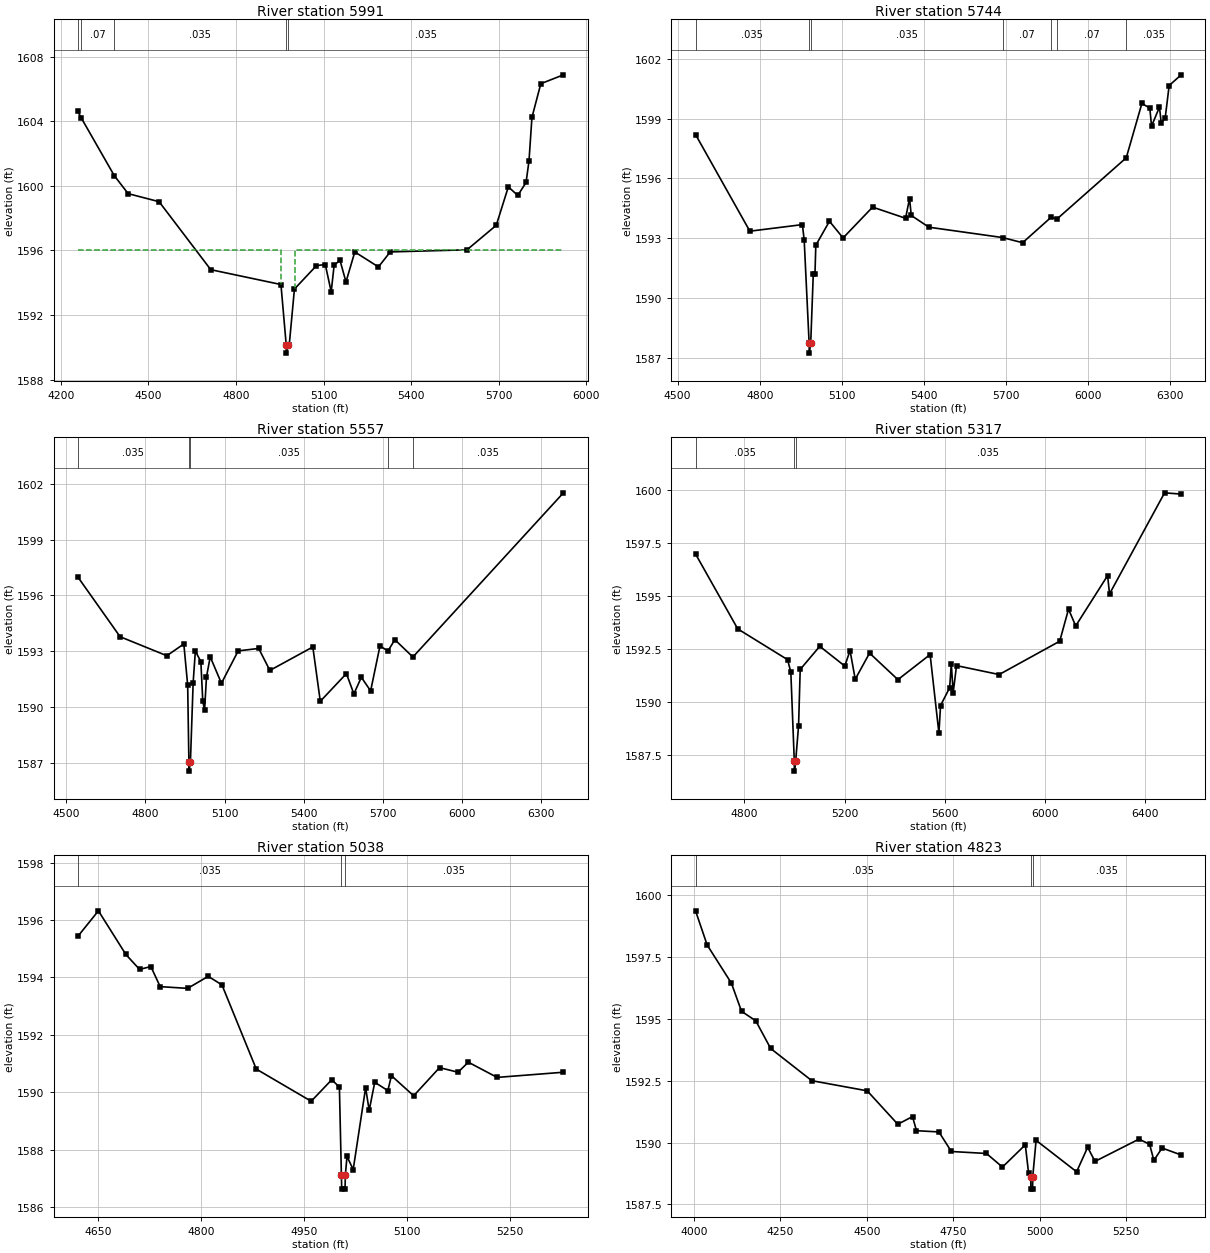
Type RM Length L Ch R = 1 ,5991    ,247,247,247
BEGIN DESCRIPTION:
Mapping XS fb1d63b1
END DESCRIPTION:
XS GIS Cut Line= 3
       1590506.3      6961842.57      1591055.36      6961341.25
      1591194.01      6960431.36
#Sta/Elev= 30
  4258.1 1604.61  4270.2  1604.2  4383.2 1600.63  4430.5 1599.52  4536.6 1599.02
  4713.6 1594.81  4954.1 1593.89  4972.2 1590.14  4972.7 1589.64    4978 1590.14
  4982.5 1590.15  5000.3 1593.61  5075.7 1595.06    5106 1595.13  5126.3 1593.44
  5136.4  1595.1  5156.6 1595.38  5176.9 1594.05  5207.2 1595.91  5288.1 1594.98
  5328.6 1595.91  5591.6 1596.04  5691.9 1597.56  5733.2 1599.94  5765.6 1599.41
  5793.9 1600.21    5804 1601.54  5814.1 1604.24  5844.5 1606.33    5922 1606.88
#Mann= 5 ,-1 , 0
  4258.1    .035       0  4270.2     .07       0  4383.2    .035       0
  4972.2    .035       0    4978    .035       0
#XS Ineff= 2 , 0
       0    4954    1596    5001       0    1596
Permanent Ineff=
       F       F
Bank Sta=4972.2,4978
XS Rating Curve= 0 ,0
Exp/Cntr=0.3,0.1

Type RM Length L Ch R = 1 ,5744    ,187,187,187
BEGIN DESCRIPTION:
Mapping XS d36f0639
END DESCRIPTION:
XS GIS Cut Line= 3
      1590880.03      6961812.97      1591207.18       6961527.9
      1592026.49      6960467.97
#Sta/Elev= 30
  4565.3 1598.21  4763.7 1593.35  4955.5 1593.68  4962.1 1592.92  4980.2 1587.72
  4980.7 1587.22    4986 1587.72  4995.3 1591.18  5001.5 1591.18  5004.6 1592.64
  5054.4 1593.85  5104.2 1593.01    5212 1594.56  5332.4    1594  5346.9 1594.99
  5353.3 1594.14  5417.6 1593.55  5686.6 1593.03  5759.9 1592.77    5864 1594.05
  5885.3 1593.96  6138.5 1597.04  6195.5 1599.77  6224.5 1599.54  6230.8 1598.63
  6259.8 1599.59  6266.1  1598.8  6280.6 1599.03  6295.1 1600.67  6338.9 1601.21
#Mann= 7 ,-1 , 0
  4565.3    .035       0  4980.2    .035       0    4986    .035       0
  5686.6     .07       0    5864    .035       0  5885.3     .07       0
  6138.5    .035       0
Bank Sta=4980.2,4986
XS Rating Curve= 0 ,0
Exp/Cntr=0.3,0.1

Type RM Length L Ch R = 1 ,5557    ,240,240,240
BEGIN DESCRIPTION:
Mapping XS f1066868
END DESCRIPTION:
XS GIS Cut Line= 3
      1590986.42      6961912.77      1591350.41      6961638.58
       1592342.8      6960672.47
#Sta/Elev= 30
  4543.7 1596.99    4704 1593.78    4881 1592.76  4945.5 1593.39  4960.1 1591.18
  4964.7 1587.06  4965.2 1586.56  4970.5 1587.06  4980.9 1591.32  4989.2 1593.01
  5010.1 1592.44  5017.3 1590.32  5024.2 1589.85  5031.4 1591.62  5045.6  1592.7
    5088 1591.28  5151.6 1593.02  5229.3 1593.15  5271.7 1591.97  5434.5 1593.23
  5462.8 1590.31  5561.8  1591.8  5590.1 1590.71  5618.4  1591.6  5653.6 1590.87
  5689.1 1593.29    5719 1593.01  5745.5 1593.62  5813.8 1592.69  6384.4 1601.51
#Mann= 5 ,-1 , 0
  4543.7    .035       0  4964.7    .035       0  4970.5    .035       0
    5719     .07       0  5813.8    .035       0
Bank Sta=4964.7,4970.5
XS Rating Curve= 0 ,0
Exp/Cntr=0.3,0.1

Type RM Length L Ch R = 1 ,5317    ,279,279,279
BEGIN DESCRIPTION:
Mapping XS 500d9414
END DESCRIPTION:
XS GIS Cut Line= 3
      1591035.94      6961998.68      1591399.69      6961846.46
      1592581.03      6960850.77
#Sta/Elev= 30
  4604.7 1596.99  4773.3 1593.46  4972.3 1592.01  4985.3 1591.42    4999 1587.26
  4999.5 1586.76  5004.8 1587.26  5016.2  1588.9  5022.7 1591.55  5100.8 1592.64
  5200.8 1591.71  5221.7 1592.44  5242.5 1591.09  5299.7 1592.32  5412.9 1591.07
  5541.5 1592.25  5576.7 1588.55  5583.2 1589.85  5619.6 1590.69  5626.1 1591.81
  5633.7 1590.46    5647 1591.73  5817.3 1591.31  6059.1 1592.88  6094.3 1594.39
  6122.9  1593.6  6250.3 1595.97  6258.1 1595.11  6477.9 1599.87    6544 1599.81
#Mann= 3 ,-1 , 0
  4604.7    .035       0    4999    .035       0  5004.8    .035       0
Bank Sta=4999,5004.8
XS Rating Curve= 0 ,0
Exp/Cntr=0.3,0.1

Type RM Length L Ch R = 1 ,5038    ,215,215,215
BEGIN DESCRIPTION:
Mapping XS 47c902c3
END DESCRIPTION:
XS GIS Cut Line= 3
        1591075.       6962071.6      1591451.78      6962076.49
      1591767.18      6961977.12
#Sta/Elev= 30
  4620.2 1595.43  4650.2 1596.32  4690.2  1594.8  4710.2 1594.28  4726.6 1594.38
  4740.2 1593.68  4780.2 1593.62  4810.2 1594.04  4830.2 1593.74  4880.2 1590.81
  4960.2 1589.69  4990.2 1590.44  5001.3 1590.18  5004.2 1587.13  5004.7 1586.63
  5009.5 1586.63    5010 1587.13  5012.4 1587.77  5021.4 1587.31  5039.5 1590.16
  5044.7 1589.37  5052.8 1590.35  5071.9 1590.06  5077.1 1590.58  5109.5 1589.88
  5147.2 1590.86  5174.2  1590.7  5189.1 1591.05  5231.1 1590.52  5327.7  1590.7
#Mann= 3 ,-1 , 0
  4620.2    .035       0  5004.2    .035       0    5010    .035       0
Bank Sta=5004.2,5010
XS Rating Curve= 0 ,0
Exp/Cntr=0.3,0.1

Type RM Length L Ch R = 1 ,4823    ,430,430,430
BEGIN DESCRIPTION:
Mapping XS b92272a8
END DESCRIPTION:
XS GIS Cut Line= 3
      1590533.91      6961913.86      1591456.77       6962291.2
      1591839.16      6962153.36
#Sta/Elev= 30
  4004.9 1599.36  4038.5 1597.98  4108.5 1596.44  4137.9  1595.3  4178.9 1594.92
  4222.1  1593.8  4340.9  1592.5  4501.1 1592.09  4589.5 1590.74    4632 1591.05
  4643.5 1590.48  4708.3 1590.43  4744.3 1589.64  4845.7 1589.56    4892 1589.01
    4958 1589.91  4967.6 1588.76  4973.7 1588.62  4974.2 1588.12    4979 1588.12
  4979.5 1588.62  4989.2 1590.09  5106.3 1588.82  5138.2 1589.81  5159.5 1589.24
  5286.6 1590.14  5317.3 1589.93  5329.6 1589.28  5353.3 1589.78  5408.4  1589.5
#Mann= 3 ,-1 , 0
  4004.9    .035       0  4973.7    .035       0  4979.5    .035       0
Bank Sta=4973.7,4979.5
XS Rating Curve= 0 ,0
Exp/Cntr=0.3,0.1

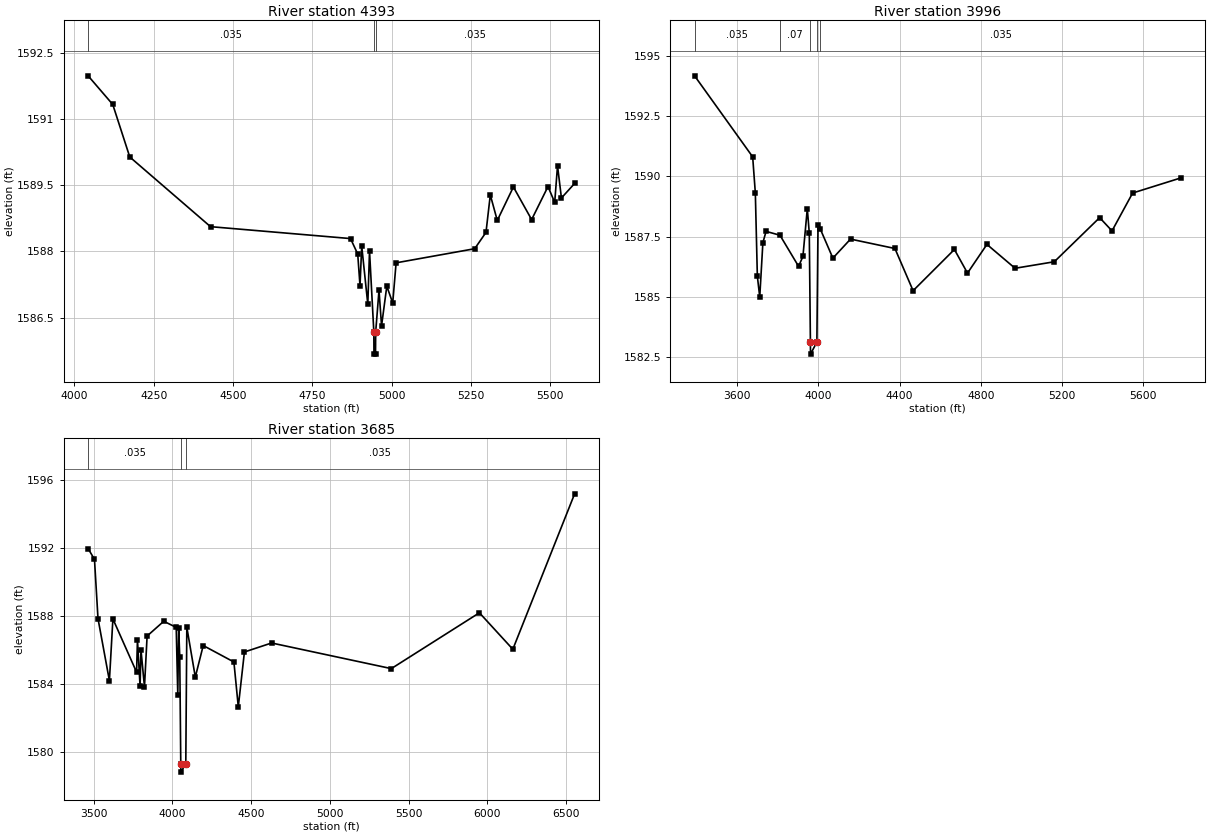
Type RM Length L Ch R = 1 ,4393    ,397,397,397
BEGIN DESCRIPTION:
Mapping XS cec90536
END DESCRIPTION:
XS GIS Cut Line= 3
      1590692.52       6962322.8      1591584.83       6962668.4
       1591895.4      6962182.58
#Sta/Elev= 30
  4043.1 1591.98  4120.8 1591.33  4174.4 1590.14  4428.9 1588.56  4870.2 1588.29
  4892.9 1587.94  4900.1 1587.22  4905.5 1588.12  4924.7  1586.8  4930.1 1588.01
  4943.7 1586.17  4944.1 1585.67    4949 1585.67  4949.5 1586.17    4960 1587.12
    4968 1586.31  4984.6 1587.21  5003.2 1586.83  5013.9 1587.74  5261.6 1588.06
  5297.2 1588.43  5310.8 1589.28  5332.8  1588.7  5383.6 1589.46  5441.1 1588.72
  5492.7 1589.47  5513.8 1589.11  5522.7 1589.94    5535 1589.21  5576.6 1589.54
#Mann= 3 ,-1 , 0
  4043.1    .035       0  4943.7    .035       0  4949.5    .035       0
Bank Sta=4943.7,4949.5
XS Rating Curve= 0 ,0
Exp/Cntr=0.3,0.1

Type RM Length L Ch R = 1 ,3996    ,311,311,311
BEGIN DESCRIPTION:
Mapping XS cc9c37e3
END DESCRIPTION:
XS GIS Cut Line= 3
      1591120.23      6964104.22      1591931.86      6962728.36
      1592066.38      6961942.91
#Sta/Elev= 30
  3391.4 1594.17  3677.3 1590.81  3690.4 1589.31  3700.3 1585.86  3712.1    1585
  3727.5 1587.25  3743.2 1587.72  3811.6 1587.56  3903.2 1586.27  3924.6 1586.68
  3946.1 1588.66  3955.9 1587.65  3961.4 1583.13  3961.9 1582.63  3993.3 1583.13
  3998.8 1587.99    4010 1587.82    4072 1586.61  4158.8  1587.4  4377.4 1587.01
  4466.8 1585.26  4670.1 1586.97  4734.5 1585.99  4830.1 1587.18  4968.6 1586.19
  5161.7 1586.46  5384.9 1588.29  5445.7 1587.74  5547.2 1589.31  5785.7 1589.94
#Mann= 5 ,-1 , 0
  3391.4    .035       0  3811.6     .07       0  3961.4    .035       0
  3993.3     .07       0    4010    .035       0
Bank Sta=3961.4,3993.3
XS Rating Curve= 0 ,0
Exp/Cntr=0.3,0.1

Type RM Length L Ch R = 1 ,3685    ,0,0,0
BEGIN DESCRIPTION:
Mapping XS 03414fdd
END DESCRIPTION:
XS GIS Cut Line= 3
       1591510.5      6964106.67      1592204.93       6962738.3
      1593359.24      6961698.62
#Sta/Elev= 30
  3465.5 1591.96  3505.9 1591.33  3528.2 1587.84  3600.6 1584.18  3622.8 1587.82
  3773.1 1584.68  3778.7 1586.59  3795.3 1583.84  3800.9    1586  3823.2 1583.81
  3839.9 1586.81  3945.6 1587.68  4024.7 1587.32  4034.6 1583.35  4040.2 1587.27
  4047.1  1585.6  4053.6 1579.29  4054.1 1578.79  4085.5 1579.29    4092 1587.33
  4145.9 1584.39  4196.1 1586.25  4390.8 1585.28  4418.7 1582.64  4457.6 1585.87
  4630.1  1586.4    5390 1584.89  5949.1 1588.18  6161.3 1586.03  6553.5 1595.19
#Mann= 3 ,-1 , 0
  3465.5    .035       0  4053.6    .035       0  4085.5    .035       0
Bank Sta=4053.6,4085.5
XS Rating Curve= 0 ,0
Exp/Cntr=0.3,0.1

Chan Stop Cuts=-1
Use User Specified Reach Order=0
Composite Channel Slope=5