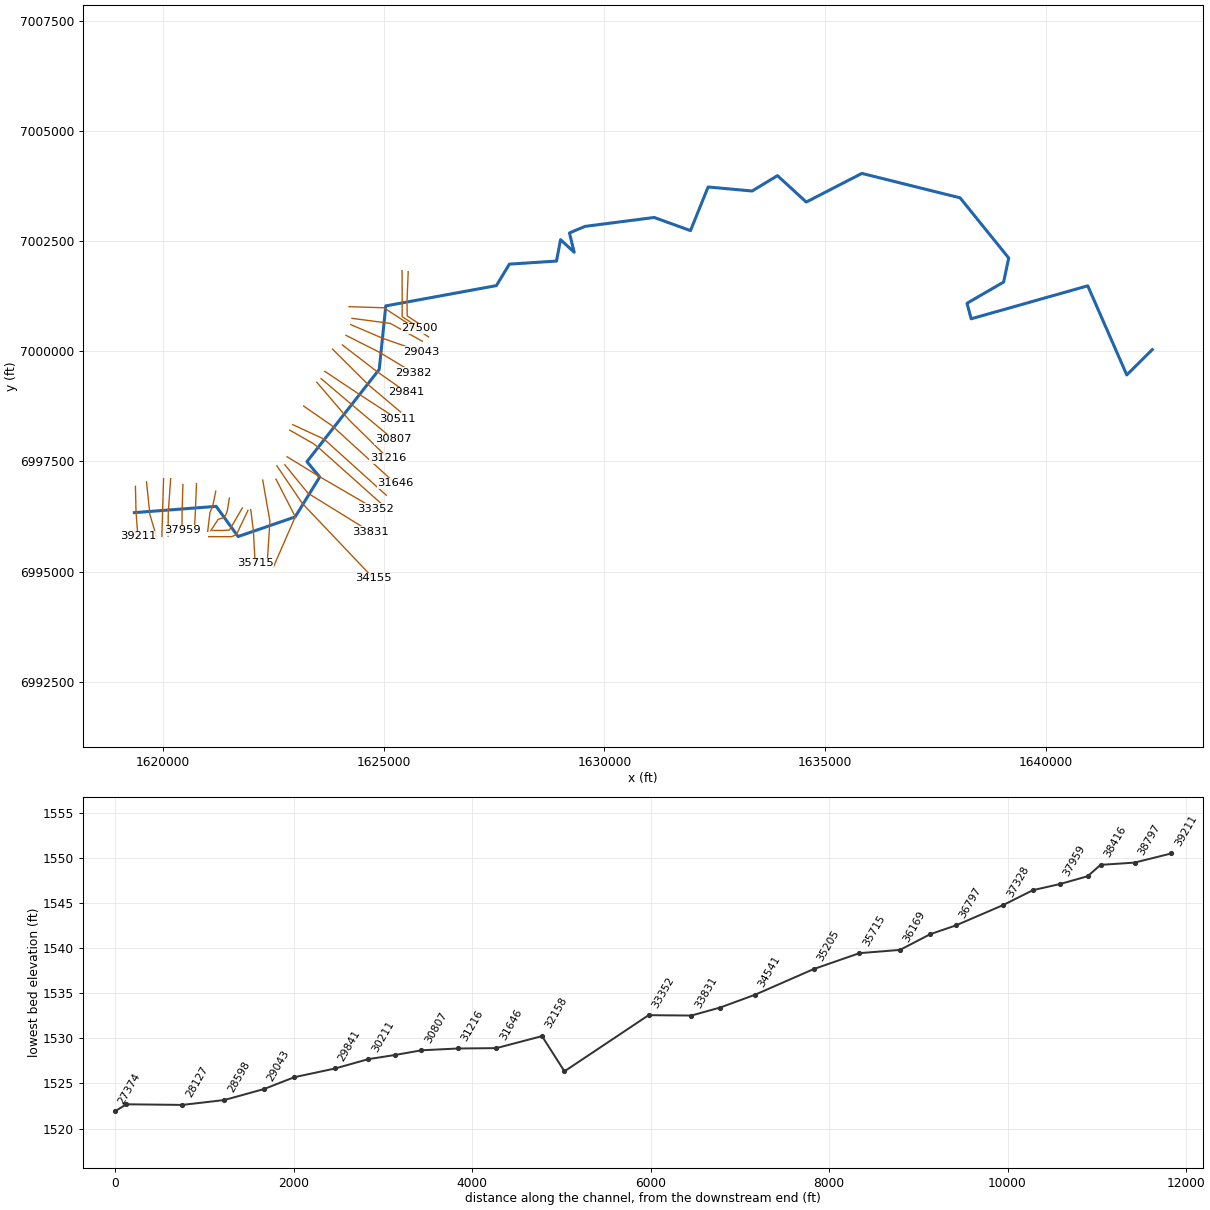
--- Pinto Creek.prj (project) ---

Proj Title=Pinto Creek Base Level Engineering
Current Plan=p01
Default Exp/Contr=0.3,0.1
English Units
Geom File=g01
Flow File=f01
Plan File=p01
Y Axis Title=Elevation
X Axis Title(PF)=Main Channel Distance
X Axis Title(XS)=Station
BEGIN DESCRIPTION:
Pinto Creek
END DESCRIPTION:
DSS Export Rating Curves= 0
DSS Export Rating Curve Sorted= 0
DSS Export Volume Flow Curves= 0
DXF OffsetX= 0
DXF OffsetY= 0
DXF ScaleX= 1
DXF ScaleY= 10

--- Pinto Creek.p01 (plan) ---

Plan Title=Multiple Run
Short Identifier=Multiple
Geom File=g01
Flow File=f01
Subcritical Flow
K Sum by GR= 0
Std Step Tol= 0.01
Critical Tol= 0.01
Num of Std Step Trials= 20
Max Error Tol= 0.3
Flow Tol Ratio= 0.001
Split Flow NTrial= 30
Split Flow Tol= 0.02
Split Flow Ratio= 0.02
Log Output Level= 0
Friction Slope Method= 1
Unsteady Friction Slope Method= 2
Unsteady Bridges Friction Slope Method= 1
Parabolic Critical Depth
Global Vel Dist=  1 , 1 , 1
Global Log Level= 0
CheckData=True
Encroach Param= -1, 0, 0, 0
BEGIN DESCRIPTION:
Multiple Run
END DESCRIPTION:

--- Pinto Creek.f01 (steady flow) ---

Flow Title=Multiple
Number of Profiles=7
Profile Names=10-year,25-year,50-year,1pct_min,100-year,1pct_plu,500-year
River Rch & RM= Pinto Creek,Reach-1,39211
     202     274     332     201     401     799     589
River Rch & RM= Pinto Creek,Reach-1,38416
     226     308     375     227     453     903     669
River Rch & RM= Pinto Creek,Reach-1,35715
     337     467     574     351     701    1398    1057
River Rch & RM= Pinto Creek,Reach-1,33831
     492     696     866     536    1069    2133    1649
River Rch & RM= Pinto Creek,Reach-1,28598
     568     806    1007     624    1245    2484    1930
River Rch & RM= Pinto Creek,Reach-1,27500
     710    1013    1269     788    1573    3139    2449
River Rch & RM= Pinto Creek,Reach-1,20563
     705    1005    1258     780    1557    3107    2419
River Rch & RM= Pinto Creek,Reach-1,19325
     797    1139    1429     888    1771    3535    2761
River Rch & RM= Pinto Creek,Reach-1,15867
     855    1223    1536     955    1905    3802    2973
River Rch & RM= Pinto Creek,Reach-1,14967
    1159    1679    2126    1333    2659    5305    4216
River Rch & RM= Pinto Creek,Reach-1,9369
    1259    1827    2316    1452    2898    5782    4601
River Rch & RM= Pinto Creek,Reach-1,6314
    1358    1976    2509    1577    3146    6277    5011
Boundary for River Rch & Prof#=Pinto Creek,Reach-1,1
Up Type=0
Dn Type=3
Dn Slope=0.005
Boundary for River Rch & Prof#=Pinto Creek,Reach-1,2
Up Type=0
Dn Type=3
Dn Slope=0.005
Boundary for River Rch & Prof#=Pinto Creek,Reach-1,3
Up Type=0
Dn Type=3
Dn Slope=0.005
Boundary for River Rch & Prof#=Pinto Creek,Reach-1,4
Up Type=0
Dn Type=3
Dn Slope=0.005
Boundary for River Rch & Prof#=Pinto Creek,Reach-1,5
Up Type=0
Dn Type=3
Dn Slope=0.005
Boundary for River Rch & Prof#=Pinto Creek,Reach-1,6
Up Type=0
Dn Type=3
Dn Slope=0.005
Boundary for River Rch & Prof#=Pinto Creek,Reach-1,7
Up Type=0
Dn Type=3
Dn Slope=0.005

--- Pinto Creek.g01 (geometry) ---

Geom Title=Existing Conditions

River Reach=Pinto Creek,Reach-1
Reach XY= 30
      1619355.00      6996338.00      1621208.61      6996480.54
      1621705.00      6995795.56      1622997.05      6996240.82
      1623553.90      6997147.64      1623263.84      6997494.94
      1624901.25      6999589.55      1625048.95      7001030.55
      1627553.54      7001491.54      1627848.33      7001979.03
      1628915.00      7002048.63      1629006.56      7002534.58
      1629315.06      7002249.10      1629208.37      7002686.78
      1629560.85      7002835.96      1631127.98      7003038.25
      1631948.89      7002739.80      1632348.53      7003730.31
      1633344.50      7003639.19      1633918.82      7003987.56
      1634570.16      7003388.38      1635829.88      7004038.30
      1638053.42      7003484.33      1639154.94      7002117.97
      1639038.36      7001571.32      1638210.46      7001090.45
      1638305.00      7000738.00      1640944.50      7001486.78
      1641828.13      6999464.15      1642405.00      7000038.00

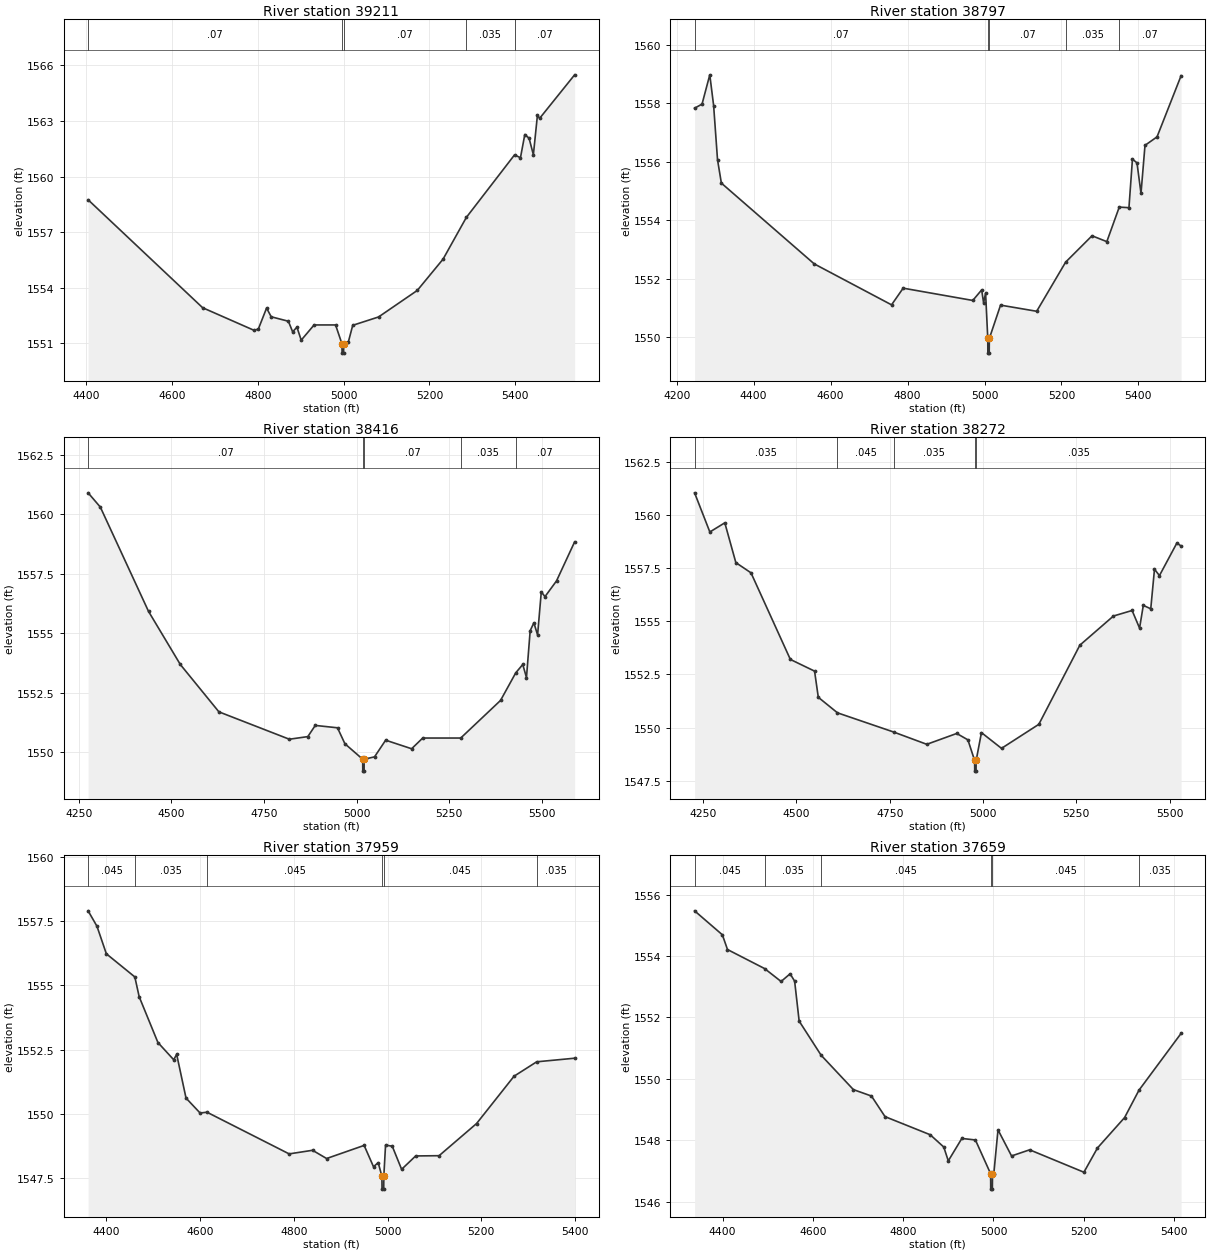
Type RM Length L Ch R = 1,39211,414,414,414
BEGIN DESCRIPTION:
Pinto Creek 71.0
END DESCRIPTION:
XS GIS Cut Line= 3
      1619380.00      6996934.89      1619394.18      6996339.06
      1619436.46      6995802.12
#Sta/Elev= 30
  4404.0 1558.75  4671.0 1552.93  4791.0 1551.71  4801.0 1551.78  4820.2 1552.91
  4831.0 1552.44  4871.0 1552.20  4881.0 1551.63  4891.0 1551.88  4901.0 1551.18
  4931.0 1552.00  4981.1 1552.00  4996.0 1550.98  4996.3 1550.48  4999.8 1550.48
  5000.0 1550.98  5011.1 1551.10  5021.1 1551.98  5081.3 1552.43  5171.6 1553.86
  5231.8 1555.55  5286.1 1557.80  5398.4 1561.17  5412.3 1561.02  5422.4 1562.27
  5432.4 1562.07  5442.4 1561.18  5451.9 1563.32  5456.9 1563.14  5538.6 1565.49
#Mann=5,-1,0
  4404.0    0.07       0  4996.0    0.07       0  5000.0    0.07       0
  5286.1   0.035       0  5398.4    0.07       0
Bank Sta=4996,5000
Exp/Cntr=0.3,0.1

Type RM Length L Ch R = 1,38797,381,381,381
BEGIN DESCRIPTION:
Mapping XS d8722ef7
END DESCRIPTION:
XS GIS Cut Line= 3
      1619631.23      6997037.25      1619707.19      6996297.22
      1619854.76      6995798.10
#Sta/Elev= 30
  4246.5 1557.83  4265.9 1557.97  4286.0 1558.97  4296.0 1557.92  4306.1 1556.07
  4316.1 1555.27  4557.4 1552.51  4758.4 1551.11  4788.6 1551.68  4969.5 1551.26
  4992.6 1551.62  4997.6 1551.18  5002.8 1551.51  5008.5 1549.96  5008.7 1549.46
  5012.2 1549.46  5012.5 1549.96  5041.7 1551.10  5135.6 1550.89  5210.9 1552.57
  5279.4 1553.47  5317.9 1553.27  5350.2 1554.45  5375.4 1554.43  5384.5 1556.09
  5396.3 1555.96  5406.7 1554.92  5417.1 1556.56  5448.4 1556.85  5510.9 1558.94
#Mann=5,-1,0
  4246.5    0.07       0  5008.5    0.07       0  5012.5    0.07       0
  5210.9   0.035       0  5350.2    0.07       0
Bank Sta=5008.5,5012.5
Exp/Cntr=0.3,0.1

Type RM Length L Ch R = 1,38416,144,144,144
BEGIN DESCRIPTION:
Mapping XS 2f0bdee1
END DESCRIPTION:
XS GIS Cut Line= 3
      1620017.52      6997110.98      1619995.82      6996390.54
      1619978.45      6995798.06
#Sta/Elev= 30
  4275.3 1560.90  4308.3 1560.30  4438.4 1555.92  4524.2 1553.69  4628.4 1551.70
  4818.5 1550.55  4868.5 1550.66  4888.6 1551.13  4948.6 1551.03  4968.6 1550.36
  5016.6 1549.71  5016.9 1549.21  5020.4 1549.21  5020.6 1549.71  5048.6 1549.81
  5078.6 1550.51  5148.7 1550.15  5178.7 1550.60  5281.3 1550.60  5388.8 1552.18
  5429.9 1553.34  5448.8 1553.69  5458.8 1553.14  5468.8 1555.11  5478.8 1555.44
  5488.8 1554.93  5498.8 1556.74  5508.8 1556.54  5539.9 1557.20  5588.8 1558.84
#Mann=5,-1,0
  4275.3    0.07       0  5016.6    0.07       0  5020.6    0.07       0
  5281.3   0.035       0  5429.9    0.07       0
Bank Sta=5016.6,5020.6
Exp/Cntr=0.3,0.1

Type RM Length L Ch R = 1,38272,313,313,313
BEGIN DESCRIPTION:
Mapping XS f432de07
END DESCRIPTION:
XS GIS Cut Line= 3
      1620178.10      6997108.81      1620123.85      6996340.63
      1620119.51      6995806.74
#Sta/Elev= 30
  4227.0 1561.03  4267.9 1559.19  4308.0 1559.62  4337.6 1557.75  4378.2 1557.27
  4483.7 1553.20  4548.6 1552.65  4558.6 1551.42  4610.0 1550.69  4760.2 1549.79
  4849.4 1549.21  4929.6 1549.72  4959.6 1549.42  4977.6 1548.45  4977.9 1547.95
  4981.4 1547.95  4981.7 1548.45  4995.9 1549.76  5049.7 1549.02  5149.7 1550.15
  5259.7 1553.87  5349.7 1555.24  5399.7 1555.50  5419.7 1554.67  5429.7 1555.74
  5449.7 1555.58  5459.7 1557.44  5473.0 1557.14  5519.7 1558.67  5531.0 1558.53
#Mann=5,-1,0
  4227.0   0.035       0  4610.0   0.045       0  4760.2   0.035       0
  4977.6   0.035       0  4981.7   0.035       0
Bank Sta=4977.6,4981.7
Exp/Cntr=0.3,0.1

Type RM Length L Ch R = 1,37959,300,300,300
BEGIN DESCRIPTION:
Mapping XS 5f0f350b
END DESCRIPTION:
XS GIS Cut Line= 3
      1620455.45      6996976.91      1620436.35      6996341.49
      1620436.35      6995938.69
#Sta/Elev= 30
  4360.8 1557.90  4379.7 1557.30  4399.7 1556.23  4460.5 1555.33  4469.8 1554.56
  4509.8 1552.78  4543.5 1552.11  4549.8 1552.32  4569.8 1550.62  4599.8 1550.04
  4614.6 1550.07  4789.9 1548.45  4839.9 1548.59  4869.9 1548.27  4950.0 1548.78
  4970.0 1547.95  4980.0 1548.11  4987.9 1547.58  4988.2 1547.08  4991.8 1547.08
  4992.0 1547.58  4995.7 1548.79  5010.0 1548.75  5030.0 1547.85  5060.0 1548.37
  5110.0 1548.38  5190.0 1549.63  5270.0 1551.47  5318.3 1552.03  5399.3 1552.17
#Mann=6,-1,0
  4360.8   0.045       0  4460.5   0.035       0  4614.6   0.045       0
  4987.9   0.045       0  4992.0   0.045       0  5318.3   0.035       0
Bank Sta=4987.9,4992
Exp/Cntr=0.3,0.1

Type RM Length L Ch R = 1,37659,331,331,331
BEGIN DESCRIPTION:
Mapping XS dff3a4af
END DESCRIPTION:
XS GIS Cut Line= 3
      1620762.74      6996999.47      1620736.70      6996341.49
      1620714.13      6995923.09
#Sta/Elev= 30
  4338.0 1555.47  4399.5 1554.69  4410.9 1554.21  4493.1 1553.59  4529.6 1553.17
  4549.6 1553.42  4559.6 1553.18  4569.6 1551.88  4618.2 1550.77  4689.7 1549.65
  4729.8 1549.44  4759.8 1548.77  4859.9 1548.18  4889.9 1547.78  4899.9 1547.33
  4929.9 1548.06  4960.0 1548.01  4993.7 1546.91  4993.9 1546.41  4997.5 1546.41
  4997.8 1546.91  5000.7 1546.91  5010.0 1548.34  5040.0 1547.49  5080.1 1547.69
  5200.3 1546.96  5230.3 1547.75  5290.4 1548.74  5322.2 1549.63  5415.5 1551.48
#Mann=6,-1,0
  4338.0   0.045       0  4493.1   0.035       0  4618.2   0.045       0
  4993.7   0.045       0  4997.8   0.045       0  5322.2   0.035       0
Bank Sta=4993.7,4997.8
Exp/Cntr=0.3,0.1

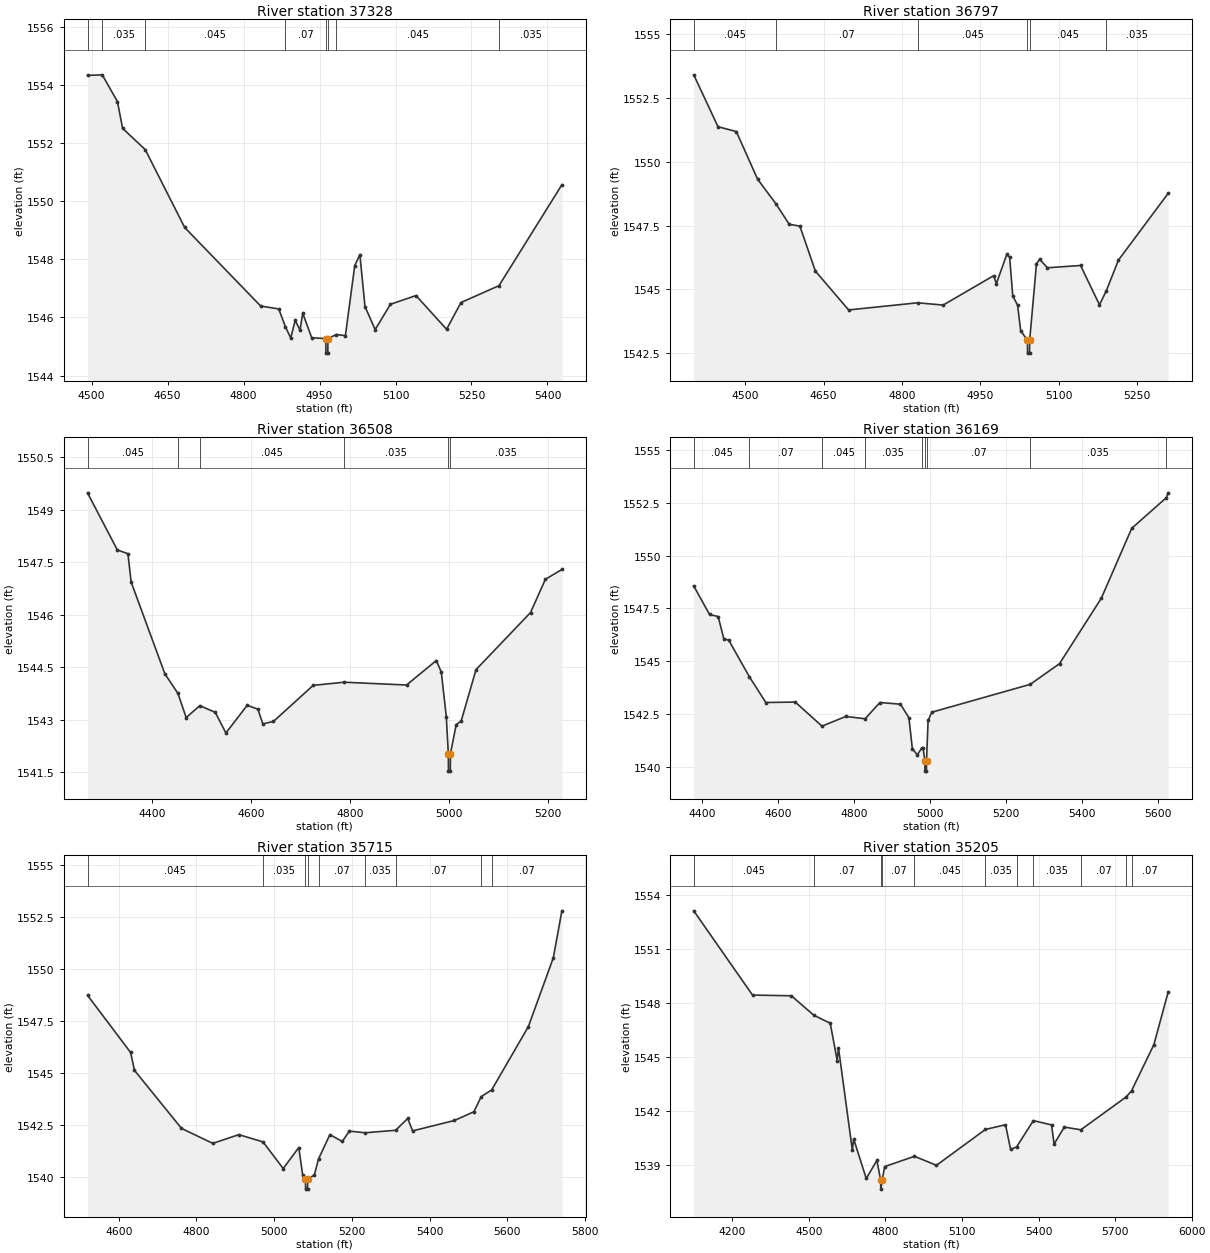
Type RM Length L Ch R = 1,37328,531,531,531
BEGIN DESCRIPTION:
Mapping XS 38a4108a
END DESCRIPTION:
XS GIS Cut Line= 4
      1621200.25      6996825.91      1621130.80      6996489.06
      1621068.30      6996339.76      1621016.34      6995912.00
#Sta/Elev= 30
  4491.8 1554.32  4520.9 1554.34  4550.9 1553.42  4561.1 1552.50  4605.7 1551.77
  4683.7 1549.09  4833.7 1546.39  4869.4 1546.29  4882.7 1545.67  4893.1 1545.29
  4901.9 1545.90  4911.4 1545.56  4916.8 1546.14  4934.5 1545.30  4962.3 1545.27
  4962.6 1544.77  4966.3 1544.77  4966.5 1545.27  4983.0 1545.41  5001.0 1545.37
  5019.5 1547.78  5029.6 1548.16  5039.7 1546.37  5059.8 1545.58  5090.0 1546.45
  5140.4 1546.75  5200.8 1545.59  5229.2 1546.51  5304.3 1547.09  5428.5 1550.56
#Mann=8,-1,0
  4491.8   0.045       0  4520.9   0.035       0  4605.7   0.045       0
  4882.7    0.07       0  4962.3   0.045       0  4966.5    0.07       0
  4983.0   0.045       0  5304.3   0.035       0
Bank Sta=4962.3,4966.5
Exp/Cntr=0.3,0.1

Type RM Length L Ch R = 1,36797,289,289,289
BEGIN DESCRIPTION:
Mapping XS bb773b17
END DESCRIPTION:
XS GIS Cut Line= 6
      1621507.35      6996668.53      1621462.22      6996385.59
      1621422.29      6996279.69      1621373.68      6996224.13
      1621253.89      6996185.94      1621085.49      6995927.27
#Sta/Elev= 30
  4401.5 1553.40  4447.9 1551.37  4483.0 1551.18  4523.6 1549.32  4558.9 1548.35
  4584.3 1547.55  4604.6 1547.48  4634.3 1545.72  4697.9 1544.20  4830.0 1544.48
  4878.8 1544.39  4975.4 1545.54  4980.7 1545.23  5000.7 1546.38  5006.1 1546.26
  5012.0 1544.75  5021.2 1544.39  5027.2 1543.39  5040.1 1543.01  5040.4 1542.51
  5044.1 1542.51  5044.4 1543.01  5057.4 1546.00  5063.4 1546.18  5078.5 1545.85
  5141.8 1545.94  5178.0 1544.40  5191.3 1544.96  5214.3 1546.15  5309.4 1548.76
#Mann=6,-1,0
  4401.5   0.045       0  4558.9    0.07       0  4830.0   0.045       0
  5040.1   0.045       0  5044.4   0.045       0  5191.3   0.035       0
Bank Sta=5040.1,5044.4
Exp/Cntr=0.3,0.1

Type RM Length L Ch R = 1,36508,339,339,339
BEGIN DESCRIPTION:
Mapping XS cb1bfe60
END DESCRIPTION:
XS GIS Cut Line= 4
      1621800.74      6996444.11      1621508.79      6995942.96
      1621357.39      6995933.62      1621131.67      6995933.62
#Sta/Elev= 30
  4269.9 1549.48  4330.0 1547.85  4351.5 1547.74  4358.0 1546.93  4426.0 1544.31
  4452.4 1543.75  4469.0 1543.06  4496.5 1543.40  4527.7 1543.21  4549.2 1542.62
  4592.2 1543.41  4613.7 1543.30  4623.7 1542.88  4645.2 1542.95  4725.4 1543.98
  4787.7 1544.07  4913.8 1543.99  4973.9 1544.69  4983.9 1544.36  4994.0 1543.09
  4998.1 1542.03  4998.4 1541.53  5002.1 1541.53  5002.4 1542.03  5014.0 1542.86
  5024.0 1542.96  5054.0 1544.43  5164.0 1546.06  5194.0 1547.01  5227.3 1547.29
#Mann=6,-1,0
  4269.9   0.045       0  4452.4    0.07       0  4496.5   0.045       0
  4787.7   0.035       0  4998.1   0.035       0  5002.4   0.035       0
Bank Sta=4998.1,5002.4
Exp/Cntr=0.3,0.1

Type RM Length L Ch R = 1,36169,454,454,454
BEGIN DESCRIPTION:
Mapping XS 14daf5b7
END DESCRIPTION:
XS GIS Cut Line= 4
      1621928.32      6996389.39      1621663.38      6995831.63
      1621552.70      6995792.56      1621039.16      6995792.56
#Sta/Elev= 30
  4378.8 1548.56  4420.3 1547.21  4443.0 1547.11  4457.8 1546.07  4471.3 1545.98
  4524.8 1544.27  4568.5 1543.04  4646.0 1543.06  4716.3 1541.92  4778.9 1542.38
  4829.8 1542.27  4868.7 1543.04  4922.8 1542.96  4945.0 1542.32  4954.0 1540.86
  4967.1 1540.56  4978.3 1540.87  4982.3 1540.88  4987.0 1540.29  4987.3 1539.79
  4991.1 1539.79  4991.4 1540.29  4995.5 1542.19  5005.2 1542.58  5264.3 1543.90
  5341.4 1544.88  5451.4 1547.98  5531.4 1551.29  5622.5 1552.74  5627.2 1552.97
#Mann=9,-1,0
  4378.8   0.045       0  4524.8    0.07       0  4716.3   0.045       0
  4829.8   0.035       0  4978.3    0.07       0  4987.0    0.07       0
  4991.4    0.07       0  5264.3   0.035       0  5622.5   0.045       0
Bank Sta=4987,4991.4
Exp/Cntr=0.3,0.1

Type RM Length L Ch R = 1,35715,510,510,510
BEGIN DESCRIPTION:
Mapping XS 6641c321
END DESCRIPTION:
XS GIS Cut Line= 3
      1621991.51      6996408.00      1622050.10      6995939.27
      1622091.26      6995191.78
#Sta/Elev= 30
  4519.6 1548.75  4630.5 1546.00  4640.5 1545.14  4761.5 1542.35  4842.1 1541.63
  4909.1 1542.05  4971.4 1541.70  5023.3 1540.42  5063.4 1541.43  5073.4 1540.11
  5080.4 1539.93  5080.9 1539.43  5085.9 1539.43  5086.4 1539.93  5103.4 1540.10
  5114.2 1540.88  5143.5 1542.05  5175.3 1541.72  5193.5 1542.22  5234.3 1542.14
  5312.7 1542.26  5343.8 1542.83  5356.3 1542.23  5464.0 1542.73  5514.0 1543.15
  5533.1 1543.88  5559.9 1544.20  5654.2 1547.24  5718.5 1550.55  5740.6 1552.81
#Mann=9,-1,0
  4519.6   0.045       0  4971.4   0.035       0  5080.4   0.035       0
  5086.4   0.035       0  5114.2    0.07       0  5234.3   0.035       0
  5312.7    0.07       0  5533.1   0.035       0  5559.9    0.07       0
Bank Sta=5080.4,5086.4
Exp/Cntr=0.3,0.1

Type RM Length L Ch R = 1,35205,664,664,664
BEGIN DESCRIPTION:
Mapping XS fe985559
END DESCRIPTION:
XS GIS Cut Line= 3
      1622262.95      6997074.75      1622425.79      6996142.87
      1622366.81      6995232.18
#Sta/Elev= 30
  4049.2 1553.11  4279.4 1548.44  4431.7 1548.40  4519.7 1547.32  4583.9 1546.88
  4611.2 1544.81  4616.2 1545.52  4670.7 1539.83  4675.7 1540.46  4725.1 1538.27
  4766.7 1539.27  4781.5 1538.18  4782.0 1537.68  4787.6 1538.18  4797.1 1538.93
  4914.0 1539.50  5000.1 1539.00  5192.0 1540.99  5270.6 1541.25  5290.7 1539.88
  5314.0 1540.02  5379.9 1541.48  5451.0 1541.24  5461.0 1540.18  5501.1 1541.12
  5565.6 1540.97  5743.3 1542.79  5764.3 1543.13  5851.9 1545.69  5907.8 1548.60
#Mann=11,-1,0
  4049.2   0.045       0  4519.7    0.07       0  4781.5   0.045       0
  4787.6    0.07       0  4914.0   0.045       0  5192.0   0.035       0
  5314.0    0.07       0  5379.9   0.035       0  5565.6    0.07       0
  5743.3   0.035       0  5764.3    0.07       0
Bank Sta=4781.5,4787.6
Exp/Cntr=0.3,0.1

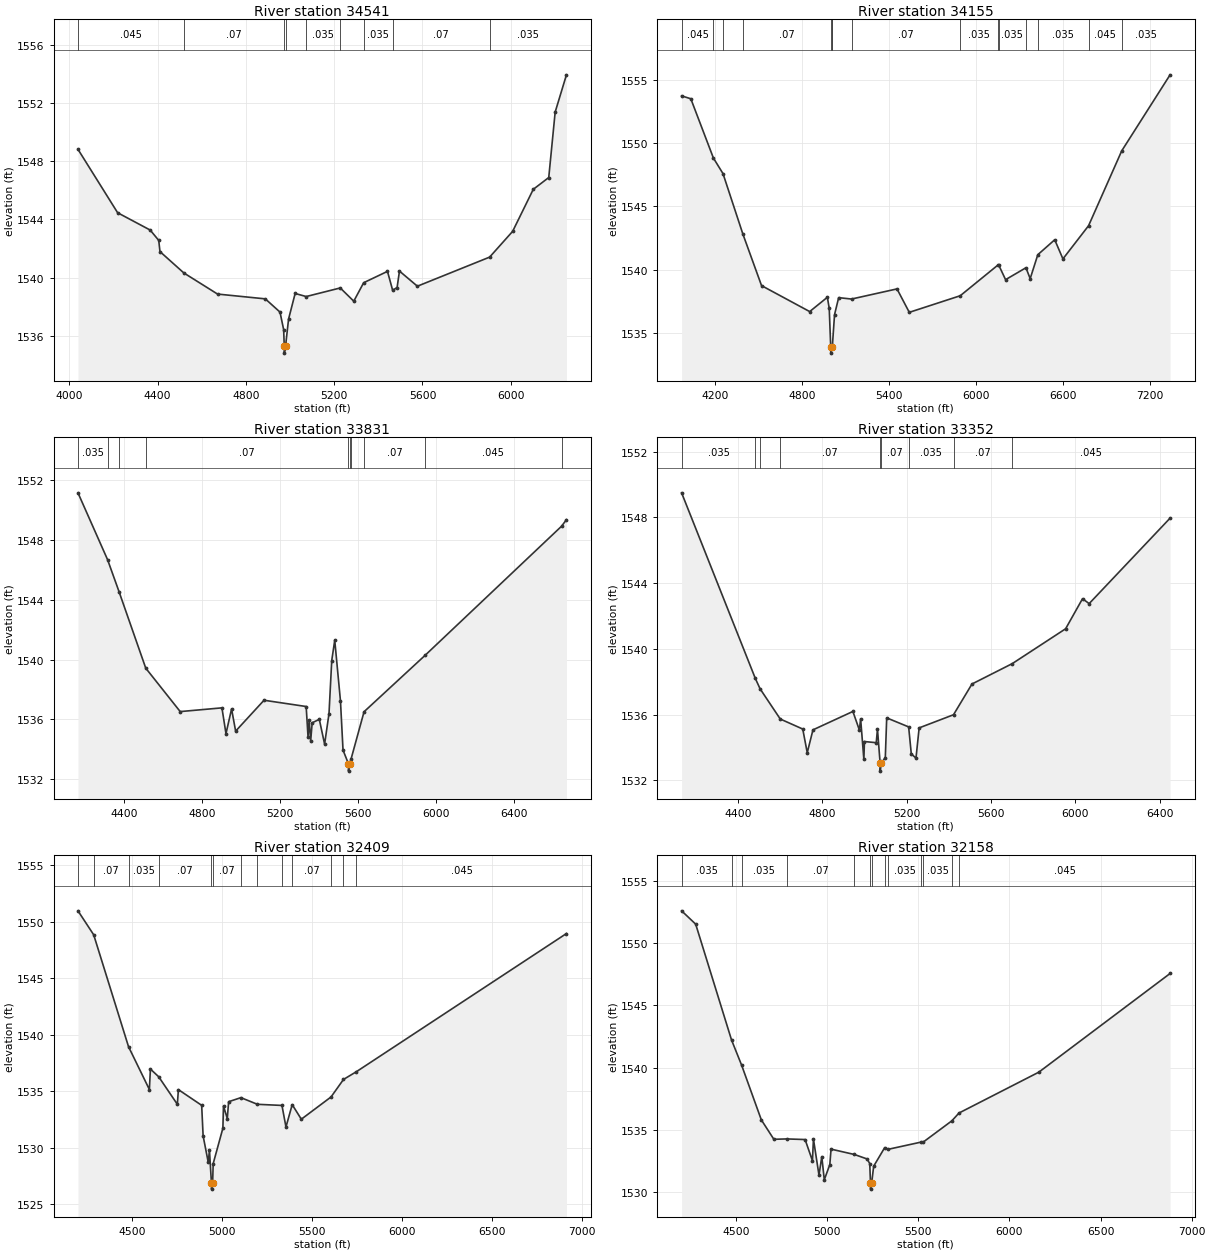
Type RM Length L Ch R = 1,34541,386,386,386
BEGIN DESCRIPTION:
Mapping XS aebc37f2
END DESCRIPTION:
XS GIS Cut Line= 3
      1622562.82      6997097.91      1623000.30      6996243.77
      1622500.31      6995094.48
#Sta/Elev= 30
  4039.4 1548.82  4219.1 1544.46  4366.5 1543.27  4405.3 1542.56  4410.9 1541.79
  4519.2 1540.32  4671.7 1538.87  4888.1 1538.54  4954.7 1537.63  4971.3 1536.42
  4973.9 1535.31  4974.4 1534.81  4980.0 1535.31  4993.5 1537.15  5023.3 1538.91
  5073.4 1538.70  5227.7 1539.29  5288.9 1538.38  5333.7 1539.65  5441.6 1540.43
  5465.0 1539.13  5485.2 1539.32  5495.9 1540.45  5577.1 1539.41  5904.4 1541.41
  6008.6 1543.18  6102.1 1546.07  6172.2 1546.88  6201.3 1551.38  6252.4 1553.94
#Mann=9,-1,0
  4039.4   0.045       0  4519.2    0.07       0  4973.9    0.07       0
  4980.0    0.07       0  5073.4   0.035       0  5227.7    0.07       0
  5333.7   0.035       0  5465.0    0.07       0  5904.4   0.035       0
Bank Sta=4973.9,4980
Exp/Cntr=0.3,0.1

Type RM Length L Ch R = 1,34155,324,324,324
BEGIN DESCRIPTION:
Mapping XS 42e96b63
END DESCRIPTION:
XS GIS Cut Line= 3
      1622581.80      6997401.99      1623160.87      6996545.84
      1624770.80      6994847.68
#Sta/Elev= 30
  3966.4 1553.72  4030.1 1553.49  4186.1 1548.81  4252.4 1547.58  4389.3 1542.82
  4518.5 1538.74  4851.1 1536.69  4973.2 1537.82  4986.0 1536.94  4996.2 1533.91
  4996.7 1533.41  5002.3 1533.91  5008.4 1534.08  5022.7 1536.45  5051.1 1537.79
  5140.0 1537.68  5454.0 1538.48  5538.9 1536.63  5890.7 1537.94  6150.8 1540.36
  6157.8 1540.33  6203.9 1539.21  6344.5 1540.15  6373.8 1539.29  6426.5 1541.18
  6543.3 1542.36  6600.0 1540.85  6777.1 1543.47  7006.1 1549.38  7340.0 1555.38
#Mann=15,-1,0
  3966.4   0.045       0  4186.1    0.07       0  4252.4   0.045       0
  4389.3    0.07       0  4996.2    0.07       0  5002.3    0.07       0
  5008.4    0.16       0  5140.0    0.07       0  5890.7   0.035       0
  6150.8    0.07       0  6157.8   0.035       0  6344.5    0.07       0
  6426.5   0.035       0  6777.1   0.045       0  7006.1   0.035       0
Bank Sta=4996.2,5002.3
Exp/Cntr=0.3,0.1

Type RM Length L Ch R = 1,33831,479,479,479
BEGIN DESCRIPTION:
Mapping XS 3476b85d
END DESCRIPTION:
XS GIS Cut Line= 3
      1622762.98      6997424.55      1623288.15      6996777.86
      1624710.84      6995897.35
#Sta/Elev= 30
  4162.6 1551.17  4314.5 1546.69  4373.2 1544.55  4510.4 1539.42  4687.1 1536.51
  4901.2 1536.76  4922.0 1535.03  4950.7 1536.69  4971.5 1535.20  5117.2 1537.27
  5333.4 1536.85  5342.9 1534.83  5348.8 1535.96  5356.5 1534.54  5364.2 1535.76
  5400.8 1535.99  5428.0 1534.33  5450.6 1536.38  5464.6 1539.93  5480.0 1541.29
  5509.4 1537.22  5522.5 1533.93  5550.1 1533.02  5550.6 1532.52  5556.4 1533.02
  5563.7 1533.33  5630.4 1536.50  5943.6 1540.28  6643.5 1548.93  6668.8 1549.37
#Mann=10,-1,0
  4162.6   0.035       0  4314.5    0.07       0  4373.2   0.035       0
  4510.4    0.07       0  5550.1    0.07       0  5556.4    0.07       0
  5563.7    0.16       0  5630.4    0.07       0  5943.6   0.045       0
  6643.5   0.035       0
Bank Sta=5550.1,5556.4
Exp/Cntr=0.3,0.1

Type RM Length L Ch R = 1,33352,943,943,943
BEGIN DESCRIPTION:
Mapping XS c71ca0b1
END DESCRIPTION:
XS GIS Cut Line= 3
      1622815.03      6997606.87      1623554.60      6997151.92
      1624806.37      6996422.47
#Sta/Elev= 30
  4131.7 1549.49  4481.4 1538.20  4503.9 1537.57  4599.7 1535.73  4706.4 1535.12
  4727.7 1533.68  4754.8 1535.07  4944.2 1536.19  4975.0 1535.06  4980.9 1535.74
  4996.3 1533.27  4999.0 1534.36  5055.0 1534.29  5060.8 1535.11  5073.3 1533.06
  5073.8 1532.56  5079.6 1533.06  5098.0 1533.38  5104.6 1535.80  5208.7 1535.25
  5221.2 1533.61  5243.5 1533.35  5258.5 1535.19  5421.5 1535.99  5509.1 1537.86
  5700.2 1539.10  5953.3 1541.22  6033.5 1543.05  6064.9 1542.75  6448.8 1547.95
#Mann=9,-1,0
  4131.7   0.035       0  4481.4    0.07       0  4503.9    0.16       0
  4599.7    0.07       0  5073.3    0.07       0  5079.6    0.07       0
  5208.7   0.035       0  5421.5    0.07       0  5700.2   0.045       0
Bank Sta=5073.3,5079.6
Exp/Cntr=0.3,0.1

Type RM Length L Ch R = 1,32409,251,251,251
BEGIN DESCRIPTION:
Mapping XS 0f37bf4c
END DESCRIPTION:
XS GIS Cut Line= 4
      1622875.80      6998210.16      1623414.02      6997901.99
      1623555.37      6997787.82      1624979.97      6996513.02
#Sta/Elev= 30
  4198.1 1550.98  4285.4 1548.86  4479.0 1538.95  4594.8 1535.16  4600.6 1536.97
  4646.5 1536.29  4750.2 1533.85  4756.0 1535.15  4885.3 1533.76  4893.3 1531.06
  4922.0 1528.70  4928.5 1529.81  4939.7 1526.84  4940.2 1526.34  4946.0 1526.84
  4949.3 1528.60  5003.1 1531.73  5006.7 1533.69  5027.6 1532.59  5035.1 1534.08
  5103.3 1534.44  5194.9 1533.85  5331.3 1533.75  5353.6 1531.84  5388.2 1533.82
  5438.9 1532.53  5603.9 1534.50  5673.1 1536.05  5745.1 1536.74  6911.7 1548.97
#Mann=13,-1,0
  4198.1   0.035       0  4285.4    0.07       0  4479.0   0.035       0
  4646.5    0.07       0  4939.7    0.07       0  4946.0    0.07       0
  5103.3    0.16       0  5194.9    0.07       0  5331.3   0.035       0
  5388.2    0.07       0  5603.9   0.035       0  5673.1    0.07       0
  5745.1   0.045       0
Bank Sta=4939.7,4946
Exp/Cntr=0.3,0.1

Type RM Length L Ch R = 1,32158,512,512,512
BEGIN DESCRIPTION:
Mapping XS 09844319
END DESCRIPTION:
XS GIS Cut Line= 3
      1622940.96      6998336.00      1623652.73      6998006.16
      1625059.00      6996734.44
#Sta/Elev= 30
  4201.1 1552.58  4278.4 1551.51  4475.2 1542.21  4530.2 1540.20  4638.6 1535.80
  4707.4 1534.24  4778.3 1534.27  4878.8 1534.22  4919.1 1532.52  4924.6 1534.26
  4955.0 1531.36  4970.4 1532.85  4984.1 1530.99  5014.5 1532.21  5021.2 1533.45
  5149.4 1533.02  5219.3 1532.66  5233.5 1532.29  5237.6 1530.74  5238.1 1530.24
  5244.2 1530.74  5255.1 1532.08  5315.5 1533.57  5335.8 1533.44  5513.7 1534.01
  5527.3 1534.02  5683.9 1535.72  5723.4 1536.35  6161.5 1539.63  6881.6 1547.55
#Mann=13,-1,0
  4201.1   0.035       0  4475.2    0.07       0  4530.2   0.035       0
  4778.3    0.07       0  5149.4   0.035       0  5237.6    0.07       0
  5244.2   0.035       0  5315.5    0.07       0  5335.8   0.035       0
  5513.7    0.07       0  5527.3   0.035       0  5683.9    0.07       0
  5723.4   0.045       0
Bank Sta=5237.6,5244.2
Exp/Cntr=0.3,0.1

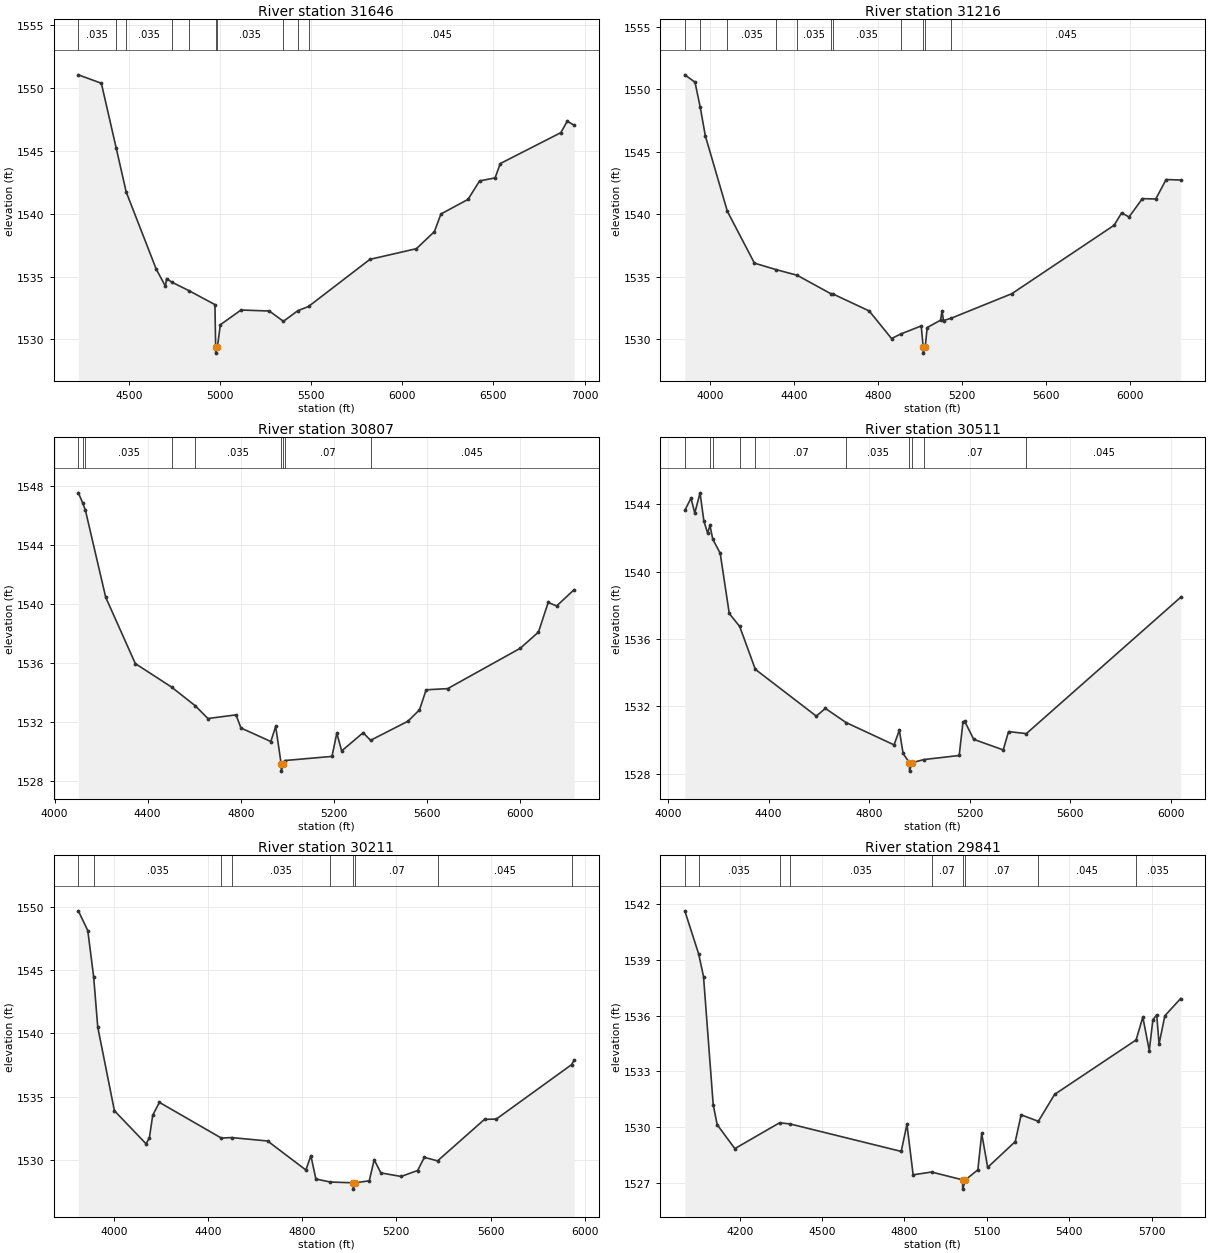
Type RM Length L Ch R = 1,31646,430,430,430
BEGIN DESCRIPTION:
Mapping XS 0d19c219
END DESCRIPTION:
XS GIS Cut Line= 3
      1623189.15      6998757.05      1623827.21      6998314.32
      1625263.87      6997003.52
#Sta/Elev= 30
  4221.5 1551.05  4347.8 1550.38  4429.6 1545.21  4484.0 1541.74  4649.1 1535.59
  4699.7 1534.23  4705.8 1534.84  4735.5 1534.55  4828.6 1533.88  4971.3 1532.77
  4975.2 1529.41  4975.7 1528.91  4984.9 1529.41  5001.0 1531.17  5114.5 1532.34
  5269.9 1532.26  5347.2 1531.44  5425.5 1532.28  5484.8 1532.62  5821.9 1536.37
  6077.2 1537.22  6175.9 1538.58  6211.7 1539.98  6360.3 1541.14  6423.8 1542.61
  6508.9 1542.85  6537.3 1543.99  6869.7 1546.45  6904.9 1547.36  6942.9 1547.04
#Mann=10,-1,0
  4221.5   0.035       0  4429.6    0.07       0  4484.0   0.035       0
  4735.5    0.07       0  4828.6   0.035       0  4975.2   0.035       0
  4984.9   0.035       0  5347.2    0.07       0  5425.5   0.035       0
  5484.8   0.045       0
Bank Sta=4975.2,4984.9
Exp/Cntr=0.3,0.1

Type RM Length L Ch R = 1,31216,409,409,409
BEGIN DESCRIPTION:
Mapping XS 66c75195
END DESCRIPTION:
XS GIS Cut Line= 3
      1623486.99      6999298.23      1624213.53      6998446.69
      1625098.98      6997574.26
#Sta/Elev= 30
  3880.0 1551.17  3928.6 1550.58  3953.6 1548.57  3978.0 1546.27  4082.7 1540.24
  4211.8 1536.08  4313.3 1535.57  4415.2 1535.11  4574.8 1533.64  4585.8 1533.61
  4758.6 1532.25  4865.1 1530.04  4908.4 1530.40  5006.5 1531.05  5015.7 1529.37
  5016.2 1528.87  5025.7 1529.37  5034.8 1530.92  5098.5 1531.51  5105.5 1532.25
  5112.7 1531.48  5149.6 1531.67  5437.9 1533.63  5925.8 1539.12  5961.2 1540.11
  5996.6 1539.78  6060.2 1541.25  6123.9 1541.22  6173.3 1542.78  6242.4 1542.74
#Mann=11,-1,0
  3880.0   0.035       0  3953.6    0.07       0  4082.7   0.035       0
  4313.3    0.07       0  4415.2   0.035       0  4574.8    0.07       0
  4585.8   0.035       0  4908.4    0.07       0  5015.7    0.07       0
  5025.7    0.07       0  5149.6   0.045       0
Bank Sta=5015.7,5025.7
Exp/Cntr=0.3,0.1

Type RM Length L Ch R = 1,30807,296,296,296
BEGIN DESCRIPTION:
Mapping XS 9a766ce0
END DESCRIPTION:
XS GIS Cut Line= 3
      1623583.29      6999381.61      1624265.62      6998800.85
      1625210.46      6998006.98
#Sta/Elev= 30
  4102.2 1547.56  4120.3 1546.90  4132.7 1546.37  4219.8 1540.47  4347.1 1535.97
  4503.2 1534.37  4604.3 1533.11  4659.0 1532.24  4779.8 1532.49  4800.7 1531.60
  4929.2 1530.68  4950.0 1531.71  4973.5 1529.17  4974.0 1528.67  4983.6 1529.17
  4989.4 1529.39  5191.9 1529.67  5212.7 1531.25  5233.5 1530.04  5325.9 1531.28
  5357.5 1530.76  5518.4 1532.06  5567.8 1532.83  5596.4 1534.19  5688.8 1534.27
  6000.9 1537.01  6079.0 1538.11  6120.7 1540.12  6157.0 1539.88  6232.3 1540.99
#Mann=9,-1,0
  4102.2   0.035       0  4120.3    0.07       0  4132.7   0.035       0
  4503.2    0.07       0  4604.3   0.035       0  4973.5    0.07       0
  4983.6   0.035       0  4989.4    0.07       0  5357.5   0.045       0
Bank Sta=4973.5,4983.6
Exp/Cntr=0.3,0.1

Type RM Length L Ch R = 1,30511,300,300,300
BEGIN DESCRIPTION:
Mapping XS cf708e2b
END DESCRIPTION:
XS GIS Cut Line= 3
      1623667.93      6999545.67      1624440.53      6999029.15
      1625315.10      6998460.57
#Sta/Elev= 30
  4066.6 1543.65  4091.3 1544.37  4106.3 1543.49  4127.3 1544.69  4142.3 1543.03
  4157.3 1542.30  4166.7 1542.75  4178.0 1541.93  4207.4 1541.10  4243.5 1537.52
  4284.9 1536.75  4347.2 1534.20  4589.8 1531.42  4625.8 1531.88  4707.8 1531.04
  4899.1 1529.71  4920.1 1530.58  4935.1 1529.20  4960.1 1528.65  4960.6 1528.15
  4970.2 1528.65  5018.8 1528.84  5158.2 1529.08  5173.3 1531.07  5180.2 1531.11
  5216.0 1530.04  5333.4 1529.41  5354.5 1530.50  5425.4 1530.38  6039.1 1538.48
#Mann=10,-1,0
  4066.6    0.07       0  4166.7   0.035       0  4178.0    0.07       0
  4284.9   0.035       0  4347.2    0.07       0  4707.8   0.035       0
  4960.1   0.035       0  4970.2   0.035       0  5018.8    0.07       0
  5425.4   0.045       0
Bank Sta=4960.1,4970.2
Exp/Cntr=0.3,0.1

Type RM Length L Ch R = 1,30211,370,370,370
BEGIN DESCRIPTION:
Mapping XS d36f3277
END DESCRIPTION:
XS GIS Cut Line= 3
      1623841.57      7000051.29      1624655.37      6999239.66
      1625385.59      6998622.11
#Sta/Elev= 30
  3849.5 1549.66  3889.6 1548.10  3914.5 1544.46  3932.0 1540.48  4002.7 1533.88
  4137.1 1531.27  4151.2 1531.74  4165.4 1533.52  4193.7 1534.54  4456.9 1531.72
  4500.2 1531.76  4653.3 1531.49  4815.9 1529.20  4837.1 1530.33  4858.3 1528.49
  4919.7 1528.25  5016.2 1528.19  5016.7 1527.69  5026.4 1528.19  5085.1 1528.35
  5105.9 1530.01  5134.5 1528.97  5220.2 1528.69  5290.5 1529.16  5319.1 1530.20
  5375.1 1529.92  5574.6 1533.20  5624.5 1533.22  5944.4 1537.52  5955.2 1537.89
#Mann=9,-1,0
  3849.5    0.07       0  3914.5   0.035       0  4456.9    0.07       0
  4500.2   0.035       0  4919.7    0.07       0  5016.2    0.07       0
  5026.4    0.07       0  5375.1   0.045       0  5944.4   0.035       0
Bank Sta=5016.2,5026.4
Exp/Cntr=0.3,0.1

Type RM Length L Ch R = 1,29841,459,459,459
BEGIN DESCRIPTION:
Mapping XS b531a236
END DESCRIPTION:
XS GIS Cut Line= 3
      1624065.82      7000144.46      1624857.92      6999534.65
      1625517.61      6999070.26
#Sta/Elev= 30
  3999.6 1541.64  4050.3 1539.31  4067.8 1538.10  4103.1 1531.20  4117.6 1530.13
  4181.9 1528.84  4344.7 1530.23  4382.7 1530.17  4788.1 1528.69  4808.9 1530.15
  4831.5 1527.43  4898.5 1527.58  5011.6 1527.16  5012.1 1526.66  5022.0 1527.16
  5067.3 1527.70  5081.3 1529.66  5103.0 1527.83  5203.6 1529.22  5224.9 1530.66
  5287.7 1530.31  5346.9 1531.76  5643.8 1534.69  5668.3 1535.92  5691.8 1534.12
  5705.0 1535.78  5718.8 1536.04  5727.5 1534.47  5748.5 1535.99  5806.0 1536.92
#Mann=9,-1,0
  3999.6    0.07       0  4050.3   0.035       0  4344.7    0.07       0
  4382.7   0.035       0  4898.5    0.07       0  5011.6    0.07       0
  5022.0    0.07       0  5287.7   0.045       0  5643.8   0.035       0
Bank Sta=5011.6,5022
Exp/Cntr=0.3,0.1

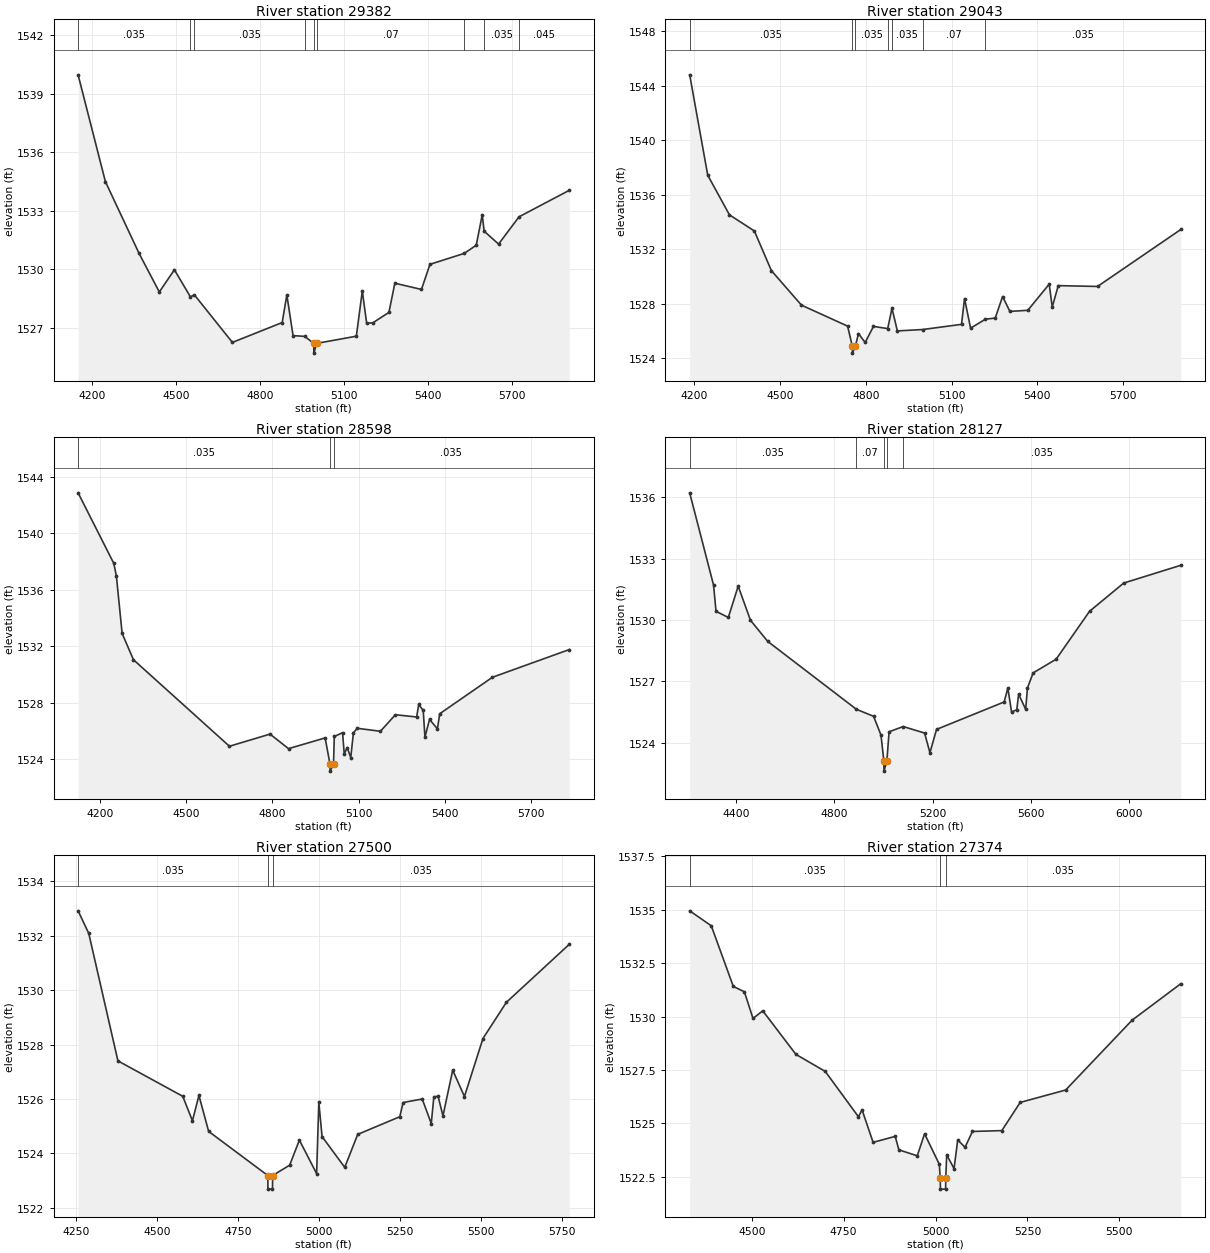
Type RM Length L Ch R = 1,29382,339,339,339
BEGIN DESCRIPTION:
Mapping XS 1f325f0e
END DESCRIPTION:
XS GIS Cut Line= 3
      1624148.13      7000363.07      1624907.69      6999976.78
      1625681.18      6999508.78
#Sta/Elev= 30
  4149.5 1539.98  4247.0 1534.50  4367.5 1530.81  4439.9 1528.83  4493.8 1529.97
  4551.1 1528.58  4565.4 1528.68  4701.2 1526.24  4879.2 1527.26  4895.9 1528.68
  4918.1 1526.59  4959.7 1526.55  4992.1 1526.19  4992.6 1525.69  5002.6 1526.19
  5144.4 1526.56  5165.7 1528.88  5181.2 1527.23  5202.6 1527.24  5260.8 1527.78
  5282.1 1529.28  5377.2 1528.96  5407.6 1530.25  5530.0 1530.81  5573.1 1531.23
  5594.6 1532.80  5601.3 1531.95  5653.0 1531.29  5726.1 1532.69  5905.7 1534.05
#Mann=9,-1,0
  4149.5   0.035       0  4551.1    0.07       0  4565.4   0.035       0
  4959.7    0.07       0  4992.1    0.07       0  5002.6    0.07       0
  5530.0   0.045       0  5601.3   0.035       0  5726.1   0.045       0
Bank Sta=4992.1,5002.6
Exp/Cntr=0.3,0.1

Type RM Length L Ch R = 1,29043,445,445,445
BEGIN DESCRIPTION:
Mapping XS 0c3a5bae
END DESCRIPTION:
XS GIS Cut Line= 3
      1624257.04      7000605.56      1625001.44      7000286.53
      1625860.40      6999989.36
#Sta/Elev= 30
  4183.3 1544.79  4246.4 1537.43  4322.5 1534.52  4409.6 1533.34  4469.2 1530.43
  4574.4 1527.90  4735.9 1526.36  4752.5 1524.88  4753.0 1524.38  4763.0 1524.88
  4773.9 1525.81  4797.4 1525.16  4826.4 1526.34  4876.2 1526.18  4891.2 1527.67
  4910.0 1526.01  4998.3 1526.11  5134.5 1526.49  5145.1 1528.38  5166.3 1526.21
  5218.3 1526.87  5252.4 1526.95  5278.3 1528.53  5303.8 1527.44  5366.5 1527.52
  5441.4 1529.44  5452.0 1527.76  5473.1 1529.33  5610.5 1529.27  5902.1 1533.45
#Mann=7,-1,0
  4183.3   0.035       0  4752.5    0.07       0  4763.0   0.035       0
  4876.2    0.07       0  4891.2   0.035       0  4998.3    0.07       0
  5218.3   0.035       0
Bank Sta=4752.5,4763
Exp/Cntr=0.3,0.1

Type RM Length L Ch R = 1,28598,471,471,471
BEGIN DESCRIPTION:
Mapping XS 81dcca19
END DESCRIPTION:
XS GIS Cut Line= 3
      1624283.16      7000748.77      1625153.35      7000633.75
      1625878.21      7000227.92
#Sta/Elev= 30
  4124.0 1542.85  4248.1 1537.86  4257.0 1536.99  4277.2 1532.90  4316.6 1531.04
  4650.4 1524.92  4791.6 1525.78  4856.0 1524.75  4983.3 1525.51  5000.2 1523.66
  5000.7 1523.16  5012.5 1523.66  5015.1 1525.61  5044.0 1525.88  5049.7 1524.37
  5060.0 1524.83  5072.4 1524.12  5081.7 1525.88  5095.3 1526.19  5175.6 1525.98
  5227.8 1527.15  5301.6 1526.99  5308.9 1527.88  5324.5 1527.45  5330.5 1525.57
  5346.5 1526.82  5373.9 1526.15  5381.9 1527.22  5565.2 1529.80  5832.5 1531.76
#Mann=3,-1,0
  4124.0   0.035       0  5000.2   0.035       0  5012.5   0.035       0
Bank Sta=5000.2,5012.5
Exp/Cntr=0.3,0.1

Type RM Length L Ch R = 1,28127,627,627,627
BEGIN DESCRIPTION:
Pinto Creek 50.0
END DESCRIPTION:
XS GIS Cut Line= 3
      1624218.04      7001013.53      1625004.64      7000988.36
      1626017.07      7000327.76
#Sta/Elev= 30
  4213.0 1536.22  4310.0 1531.71  4320.0 1530.43  4370.0 1530.13  4410.1 1531.66
  4460.1 1529.99  4530.1 1528.96  4890.6 1525.64  4960.3 1525.30  4990.4 1524.38
  5002.0 1523.12  5002.5 1522.62  5014.3 1523.12  5023.2 1524.54  5080.5 1524.80
  5167.6 1524.48  5189.2 1523.52  5216.2 1524.66  5490.8 1526.00  5505.9 1526.68
  5521.0 1525.51  5542.1 1525.62  5549.7 1526.38  5578.3 1525.64  5585.5 1526.68
  5608.6 1527.42  5702.1 1528.09  5837.8 1530.43  5976.6 1531.81  6208.9 1532.68
#Mann=5,-1,0
  4213.0   0.035       0  4890.6    0.07       0  5002.0    0.07       0
  5014.3    0.07       0  5080.5   0.035       0
Bank Sta=5002,5014.3
Exp/Cntr=0.3,0.1

Type RM Length L Ch R = 1,27500,126,126,126
BEGIN DESCRIPTION:
Mapping XS ac3a5c13
END DESCRIPTION:
XS GIS Cut Line= 4
      1625417.76      7001830.90      1625421.24      7001094.81
      1625419.50      7000787.52      1625813.63      7000527.08
#Sta/Elev= 30
  4256.7 1532.91  4289.6 1532.08  4379.6 1527.40  4579.6 1526.10  4609.6 1525.20
  4629.6 1526.13  4659.6 1524.81  4842.1 1523.19  4842.6 1522.69  4856.6 1522.69
  4857.1 1523.19  4909.6 1523.57  4939.6 1524.49  4992.8 1523.26  4999.6 1525.88
  5009.6 1524.62  5079.6 1523.49  5119.6 1524.70  5249.6 1525.35  5259.6 1525.87
  5318.7 1526.00  5346.6 1525.10  5354.6 1526.08  5367.7 1526.10  5382.7 1525.38
  5412.8 1527.06  5449.0 1526.09  5506.1 1528.22  5578.4 1529.55  5772.5 1531.68
#Mann=3,-1,0
  4256.7   0.035       0  4842.1   0.035       0  4857.1   0.035       0
Bank Sta=4842.1,4857.1
Exp/Cntr=0.3,0.1

Type RM Length L Ch R = 1,27374,321,321,321
BEGIN DESCRIPTION:
Mapping XS 168ed271
END DESCRIPTION:
XS GIS Cut Line= 4
      1625556.65      7001806.65      1625530.61      7001138.21
      1625534.08      7000803.14      1625811.88      7000620.84
#Sta/Elev= 30
  4331.1 1534.95  4389.8 1534.25  4449.8 1531.41  4479.9 1531.16  4503.4 1529.91
  4529.9 1530.27  4620.0 1528.23  4700.0 1527.43  4790.1 1525.31  4800.1 1525.63
  4830.1 1524.11  4890.2 1524.39  4900.2 1523.76  4950.2 1523.48  4970.2 1524.51
  5010.3 1523.08  5012.8 1522.42  5013.3 1521.92  5027.3 1521.92  5027.8 1522.42
  5030.3 1523.53  5050.3 1522.88  5060.3 1524.22  5080.3 1523.88  5100.3 1524.62
  5180.3 1524.66  5230.3 1525.98  5353.9 1526.56  5534.7 1529.83  5667.4 1531.54
#Mann=3,-1,0
  4331.1   0.035       0  5012.8   0.035       0  5027.8   0.035       0
Bank Sta=5012.8,5027.8
Exp/Cntr=0.3,0.1