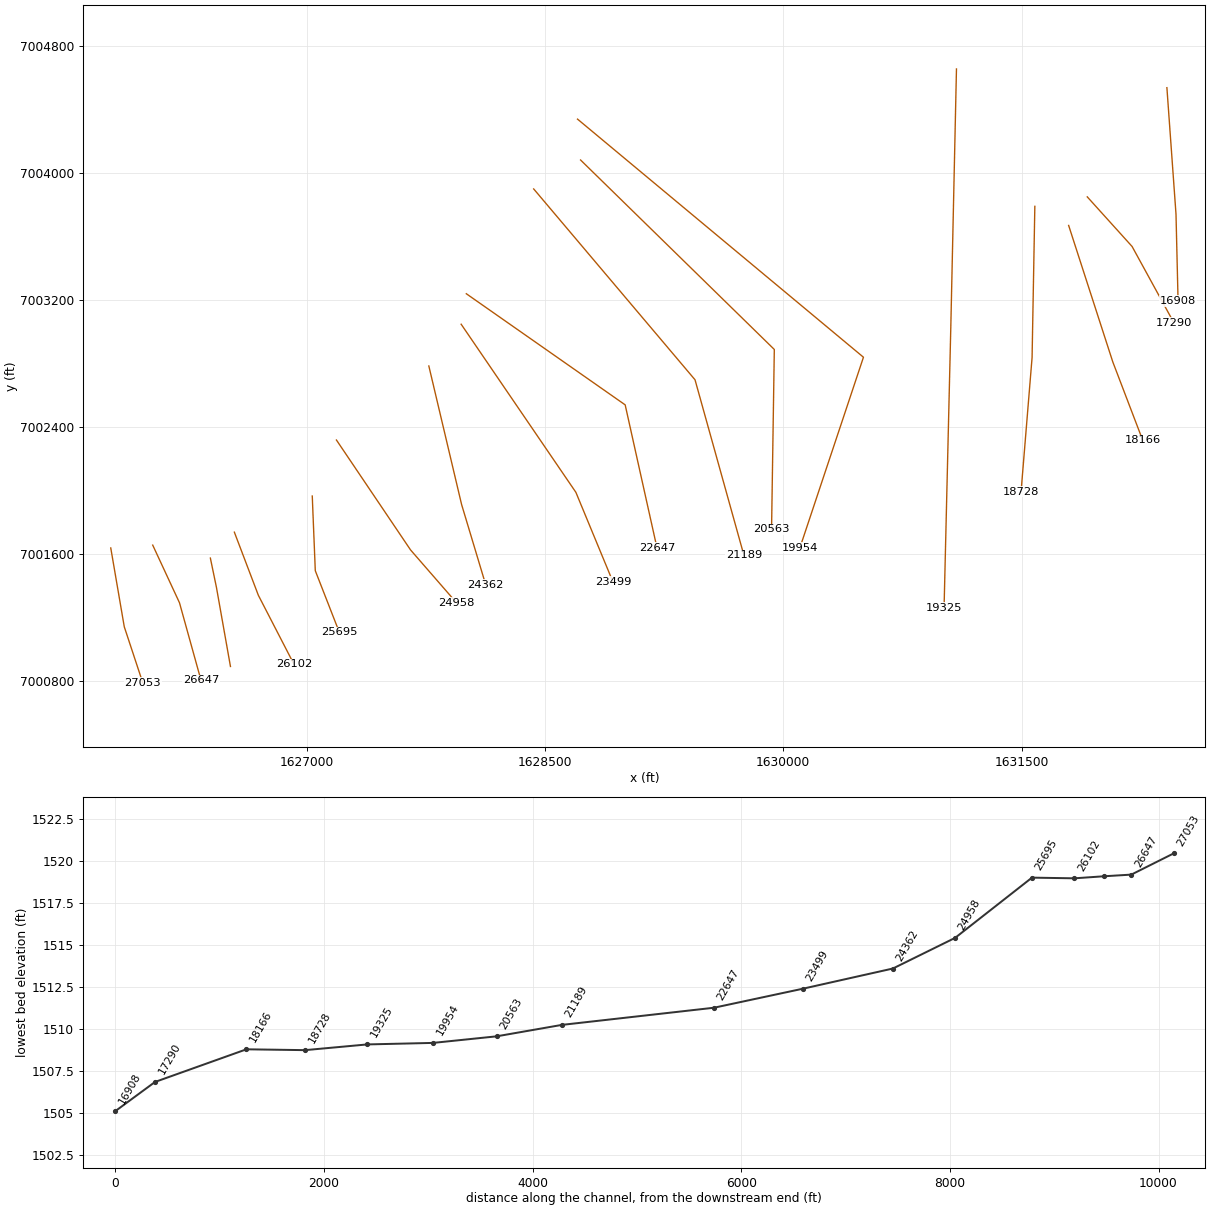
HEC-RAS study Pinto Creek.prj: Pinto Creek Base Level Engineering

--- Pinto Creek.g01 (geometry) --- (continued)

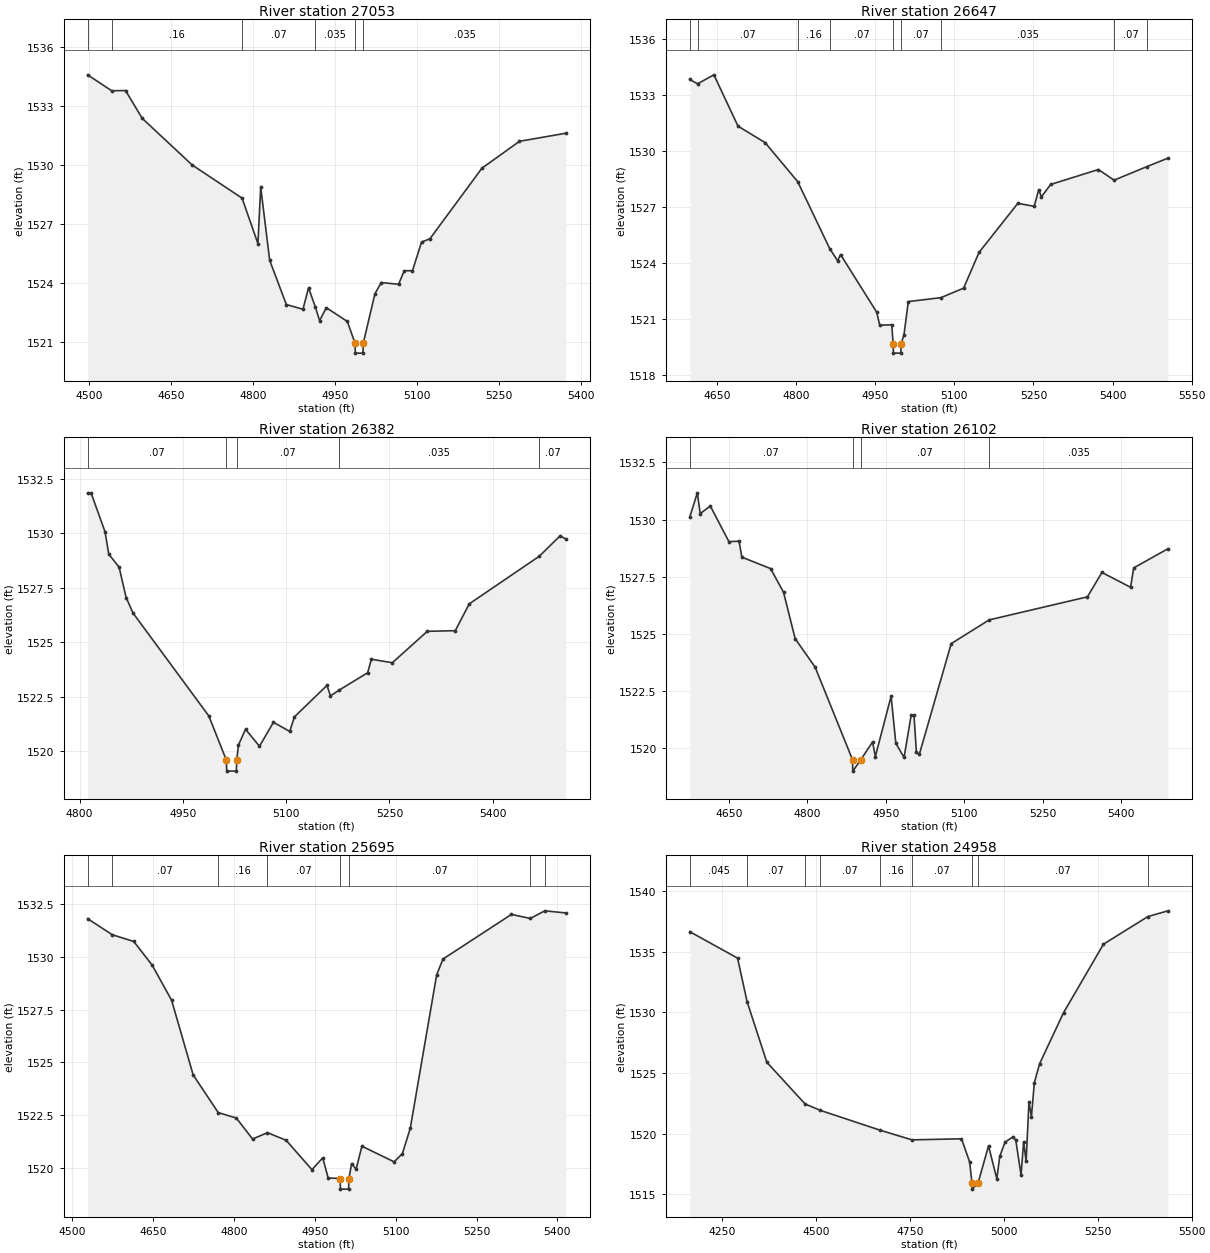
Type RM Length L Ch R = 1,27053,406,406,406
BEGIN DESCRIPTION:
Mapping XS c5ae506d
END DESCRIPTION:
XS GIS Cut Line= 3
      1625766.72      7001636.46      1625851.79      7001139.95
      1625968.12      7000787.50
#Sta/Elev= 30
  4497.2 1534.60  4541.3 1533.79  4566.7 1533.80  4597.1 1532.39  4688.4 1530.02
  4779.9 1528.33  4808.9 1526.02  4814.0 1528.89  4830.4 1525.17  4860.9 1522.92
  4891.3 1522.68  4901.5 1523.77  4913.8 1522.81  4921.8 1522.10  4934.0 1522.76
  4972.5 1522.06  4986.6 1520.95  4987.1 1520.45  5001.1 1520.45  5001.6 1520.95
  5023.0 1523.47  5034.6 1524.04  5066.2 1523.95  5076.7 1524.64  5091.7 1524.64
  5108.3 1526.10  5123.5 1526.26  5218.7 1529.85  5287.5 1531.22  5372.1 1531.63
#Mann=6,-1,0
  4497.2    0.07       0  4541.3    0.16       0  4779.9    0.07       0
  4913.8   0.035       0  4986.6   0.035       0  5001.6   0.035       0
Bank Sta=4986.6,5001.6
Exp/Cntr=0.3,0.1

Type RM Length L Ch R = 1,26647,265,265,265
BEGIN DESCRIPTION:
Mapping XS b6dd188a
END DESCRIPTION:
XS GIS Cut Line= 3
      1626030.84      7001654.42      1626199.24      7001291.57
      1626334.66      7000803.74
#Sta/Elev= 30
  4598.8 1533.84  4613.4 1533.61  4644.4 1534.09  4690.2 1531.34  4741.5 1530.46
  4803.3 1528.37  4863.9 1524.79  4878.9 1524.13  4884.4 1524.47  4953.1 1521.38
  4958.7 1520.68  4981.5 1520.71  4984.2 1519.69  4984.7 1519.19  4998.7 1519.19
  4999.2 1519.69  5004.7 1520.17  5012.9 1521.95  5074.7 1522.16  5117.8 1522.67
  5146.9 1524.58  5220.5 1527.21  5251.6 1527.05  5260.1 1527.94  5265.3 1527.56
  5282.7 1528.22  5373.2 1529.02  5403.0 1528.45  5465.4 1529.18  5505.1 1529.63
#Mann=9,-1,0
  4598.8   0.045       0  4613.4    0.07       0  4803.3    0.16       0
  4863.9    0.07       0  4984.2    0.07       0  4999.2    0.07       0
  5074.7   0.035       0  5403.0    0.07       0  5465.4   0.035       0
Bank Sta=4984.2,4999.2
Exp/Cntr=0.3,0.1

Type RM Length L Ch R = 1,26382,280,280,280
BEGIN DESCRIPTION:
Mapping XS 912ee031
END DESCRIPTION:
XS GIS Cut Line= 3
      1626393.69      7001572.83      1626431.88      7001388.79
      1626520.21      7000890.01
#Sta/Elev= 30
  4811.6 1531.85  4816.6 1531.85  4837.0 1530.06  4842.4 1529.04  4857.4 1528.44
  4867.6 1527.05  4877.8 1526.33  4987.7 1521.62  5013.2 1519.59  5013.7 1519.09
  5027.7 1519.09  5028.2 1519.59  5030.8 1520.29  5041.0 1521.01  5061.3 1520.23
  5081.6 1521.33  5105.2 1520.91  5112.1 1521.58  5159.3 1523.02  5164.4 1522.54
  5177.3 1522.81  5218.4 1523.60  5223.8 1524.22  5254.3 1524.06  5305.0 1525.50
  5345.7 1525.53  5366.0 1526.76  5467.6 1528.94  5498.0 1529.88  5506.1 1529.73
#Mann=5,-1,0
  4811.6    0.07       0  5013.2    0.07       0  5028.2    0.07       0
  5177.3   0.035       0  5467.6    0.07       0
Bank Sta=5013.2,5028.2
Exp/Cntr=0.3,0.1

Type RM Length L Ch R = 1,26102,407,407,407
BEGIN DESCRIPTION:
Mapping XS 4a67b1e2
END DESCRIPTION:
XS GIS Cut Line= 3
      1626544.72      7001736.04      1626695.77      7001338.44
      1626919.72      7000904.44
#Sta/Elev= 30
  4575.7 1530.12  4590.1 1531.17  4595.5 1530.26  4614.9 1530.59  4650.4 1529.03
  4669.8 1529.05  4675.1 1528.35  4730.0 1527.85  4754.8 1526.81  4776.9 1524.78
  4815.1 1523.53  4886.6 1519.47  4887.1 1518.97  4902.4 1519.47  4924.9 1520.25
  4930.2 1519.61  4960.3 1522.25  4969.4 1520.19  4985.1 1519.57  4998.6 1521.41
  5004.1 1521.41  5008.7 1519.79  5014.3 1519.71  5075.2 1524.56  5147.8 1525.60
  5335.4 1526.61  5363.2 1527.68  5417.9 1527.03  5424.0 1527.88  5489.4 1528.72
#Mann=4,-1,0
  4575.7    0.07       0  4886.6    0.07       0  4902.4    0.07       0
  5147.8   0.035       0
Bank Sta=4886.6,4902.4
Exp/Cntr=0.3,0.1

Type RM Length L Ch R = 1,25695,737,737,737
BEGIN DESCRIPTION:
Mapping XS 054d8196
END DESCRIPTION:
XS GIS Cut Line= 3
      1627035.18      7001963.63      1627054.28      7001493.13
      1627205.34      7001105.94
#Sta/Elev= 30
  4528.9 1531.80  4574.7 1531.04  4614.6 1530.72  4648.7 1529.60  4684.7 1527.94
  4724.7 1524.41  4771.1 1522.63  4804.8 1522.37  4834.8 1521.38  4862.4 1521.68
  4897.0 1521.32  4944.9 1519.93  4964.9 1520.49  4974.9 1519.54  4997.2 1519.51
  4997.7 1519.01  5012.9 1519.01  5013.4 1519.51  5018.5 1520.22  5026.8 1519.95
  5037.5 1521.04  5097.3 1520.30  5112.6 1520.69  5127.2 1521.89  5176.1 1529.14
  5187.8 1529.89  5314.7 1532.00  5349.8 1531.81  5376.7 1532.17  5415.4 1532.07
#Mann=8,-1,0
  4528.9   0.045       0  4574.7    0.07       0  4771.1    0.16       0
  4862.4    0.07       0  4997.2    0.07       0  5013.4    0.07       0
  5349.8    0.16       0  5376.7   0.035       0
Bank Sta=4997.2,5013.4
Exp/Cntr=0.3,0.1

Type RM Length L Ch R = 1,24958,596,596,596
BEGIN DESCRIPTION:
Mapping XS 739f5589
END DESCRIPTION:
XS GIS Cut Line= 3
      1627187.42      7002316.33      1627654.00      7001624.06
      1627942.19      7001292.54
#Sta/Elev= 30
  4163.0 1536.65  4290.2 1534.47  4315.7 1530.87  4368.2 1525.89  4470.1 1522.45
  4511.0 1521.92  4669.8 1520.29  4755.0 1519.49  4886.9 1519.58  4908.7 1517.66
  4914.8 1515.93  4915.3 1515.43  4931.0 1515.93  4958.9 1518.99  4981.0 1516.29
  4988.9 1518.14  5003.1 1519.31  5024.0 1519.74  5031.6 1519.47  5045.6 1516.59
  5052.5 1519.34  5059.1 1517.73  5066.7 1522.63  5073.3 1521.41  5081.0 1524.20
  5095.2 1525.78  5158.8 1529.97  5265.2 1535.62  5383.7 1537.90  5437.1 1538.37
#Mann=9,-1,0
  4163.0   0.045       0  4315.7    0.07       0  4470.1    0.16       0
  4511.0    0.07       0  4669.8    0.16       0  4755.0    0.07       0
  4914.8    0.07       0  4931.0    0.07       0  5383.7    0.16       0
Bank Sta=4914.8,4931
Exp/Cntr=0.3,0.1

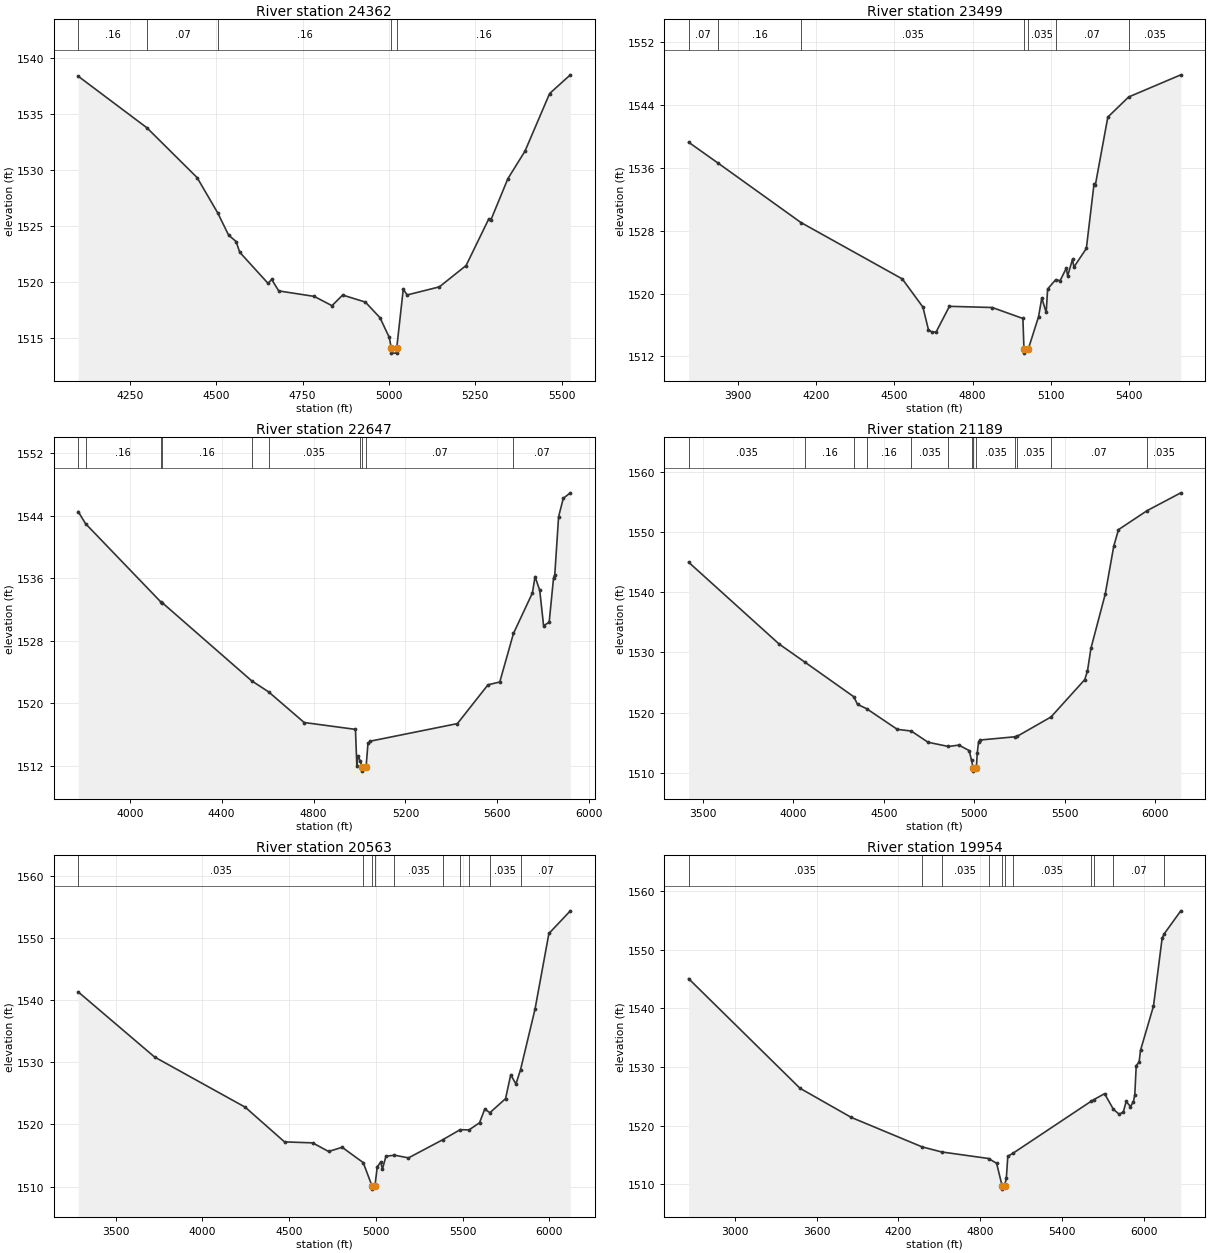
Type RM Length L Ch R = 1,24362,863,863,863
BEGIN DESCRIPTION:
Mapping XS a1eb5b2b
END DESCRIPTION:
XS GIS Cut Line= 3
      1627769.01      7002782.93      1627975.18      7001910.52
      1628127.08      7001404.89
#Sta/Elev= 30
  4100.7 1538.36  4299.6 1533.75  4444.9 1529.30  4505.0 1526.12  4536.0 1524.16
  4557.9 1523.58  4568.2 1522.63  4650.4 1519.84  4660.6 1520.20  4681.2 1519.17
  4783.9 1518.68  4835.3 1517.85  4866.2 1518.80  4932.0 1518.17  4974.3 1516.77
  5001.1 1515.01  5006.5 1514.11  5007.0 1513.61  5022.3 1513.61  5022.8 1514.11
  5041.5 1519.31  5052.9 1518.81  5146.0 1519.53  5223.4 1521.44  5289.4 1525.63
  5294.7 1525.48  5344.3 1529.20  5393.8 1531.66  5465.1 1536.81  5525.1 1538.48
#Mann=5,-1,0
  4100.7    0.16       0  4299.6    0.07       0  4505.0    0.16       0
  5006.5    0.07       0  5022.8    0.16       0
Bank Sta=5006.5,5022.8
Exp/Cntr=0.3,0.1

Type RM Length L Ch R = 1,23499,852,852,852
BEGIN DESCRIPTION:
Mapping XS 6b55bcc8
END DESCRIPTION:
XS GIS Cut Line= 3
      1627972.45      7003046.10      1628694.69      7001987.06
      1628927.33      7001424.54
#Sta/Elev= 30
  3709.3 1539.27  3822.0 1536.62  4140.9 1529.04  4530.1 1521.86  4609.4 1518.27
  4630.4 1515.41  4645.4 1515.05  4660.3 1515.12  4711.1 1518.37  4875.7 1518.22
  4993.4 1516.82  4997.5 1512.91  4998.0 1512.41  5013.9 1512.91  5053.5 1517.05
  5065.9 1519.42  5082.9 1517.59  5088.3 1520.57  5119.2 1521.76  5136.1 1521.63
  5160.0 1523.22  5165.4 1522.25  5183.9 1524.36  5189.3 1523.37  5237.1 1525.74
  5266.4 1533.90  5271.8 1533.84  5319.6 1542.47  5399.6 1545.03  5599.9 1547.85
#Mann=7,-1,0
  3709.3    0.07       0  3822.0    0.16       0  4140.9   0.035       0
  4997.5   0.035       0  5013.9   0.035       0  5119.2    0.07       0
  5399.6   0.035       0
Bank Sta=4997.5,5013.9
Exp/Cntr=0.3,0.1

Type RM Length L Ch R = 1,22647,1458,1458,1458
BEGIN DESCRIPTION:
Pinto Creek 36.0
END DESCRIPTION:
XS GIS Cut Line= 3
      1628005.02      7003237.99      1629005.00      7002538.00
      1629205.00      7001637.99
#Sta/Elev= 30
  3775.5 1544.54  3807.7 1542.99  4136.3 1532.93  4142.0 1532.85  4530.9 1522.85
  4604.4 1521.44  4759.4 1517.51  4982.6 1516.63  4988.7 1511.94  4993.1 1513.26
  5002.6 1512.63  5012.2 1511.78  5012.7 1511.28  5028.8 1511.78  5037.1 1514.83
  5047.4 1515.12  5426.4 1517.37  5559.5 1522.34  5610.8 1522.70  5670.4 1528.92
  5752.9 1534.11  5764.4 1536.21  5784.9 1534.43  5801.6 1529.90  5825.9 1530.37
  5845.1 1536.09  5850.2 1536.39  5866.9 1543.88  5887.4 1546.24  5918.1 1546.94
#Mann=10,-1,0
  3775.5   0.045       0  3807.7    0.16       0  4136.3   0.035       0
  4142.0    0.16       0  4530.9    0.07       0  4604.4   0.035       0
  5002.6    0.07       0  5012.2   0.035       0  5028.8    0.07       0
  5670.4    0.07       0
Bank Sta=5012.2,5028.8
Exp/Cntr=0.3,0.1

Type RM Length L Ch R = 1,21189,626,626,626
BEGIN DESCRIPTION:
Mapping XS 0d1de140
END DESCRIPTION:
XS GIS Cut Line= 3
      1628429.08      7003898.20      1629444.69      7002695.97
      1629752.32      7001591.09
#Sta/Elev= 30
  3420.8 1545.01  3921.6 1531.39  4066.0 1528.34  4334.1 1522.63  4354.5 1521.36
  4404.7 1520.65  4574.3 1517.21  4651.5 1516.93  4744.6 1515.06  4857.1 1514.36
  4914.9 1514.59  4972.1 1513.67  4984.7 1512.04  4994.5 1510.76  4995.0 1510.26
  5011.2 1510.76  5016.4 1513.29  5023.6 1515.14  5034.0 1515.44  5224.0 1515.97
  5236.7 1516.05  5424.1 1519.27  5610.5 1525.48  5625.7 1526.93  5644.7 1530.68
  5723.5 1539.67  5771.0 1547.69  5797.1 1550.43  5955.4 1553.59  6141.5 1556.55
#Mann=13,-1,0
  3420.8   0.035       0  4066.0    0.16       0  4334.1   0.035       0
  4404.7    0.16       0  4651.5   0.035       0  4857.1    0.07       0
  4984.7   0.035       0  4994.5   0.035       0  5011.2   0.035       0
  5224.0    0.07       0  5236.7   0.035       0  5424.1    0.07       0
  5955.4   0.035       0
Bank Sta=4994.5,5011.2
Exp/Cntr=0.3,0.1

Type RM Length L Ch R = 1,20563,609,609,609
BEGIN DESCRIPTION:
Mapping XS 799f46e2
END DESCRIPTION:
XS GIS Cut Line= 3
      1628724.19      7004080.53      1629943.82      7002886.94
      1629926.46      7001754.18
#Sta/Elev= 30
  3282.8 1541.35  3723.6 1530.86  4246.9 1522.77  4473.2 1517.19  4635.8 1517.03
  4727.7 1515.64  4805.6 1516.32  4927.3 1513.85  4978.2 1510.08  4978.7 1509.58
  4995.0 1510.08  5008.2 1513.17  5028.2 1513.93  5038.2 1512.81  5058.3 1514.87
  5107.7 1515.05  5188.3 1514.61  5388.2 1517.57  5486.1 1519.15  5538.0 1519.12
  5598.3 1520.27  5628.3 1522.47  5658.0 1521.89  5748.3 1524.15  5778.3 1528.00
  5808.3 1526.51  5834.8 1528.81  5918.4 1538.57  5998.4 1550.75  6122.2 1554.40
#Mann=10,-1,0
  3282.8   0.035       0  4927.3    0.16       0  4978.2    0.07       0
  4995.0    0.16       0  5107.7   0.035       0  5388.2    0.07       0
  5486.1   0.035       0  5538.0    0.07       0  5658.0   0.035       0
  5834.8    0.07       0
Bank Sta=4978.2,4995
Exp/Cntr=0.3,0.1

Type RM Length L Ch R = 1,19954,629,629,629
BEGIN DESCRIPTION:
Pinto Creek 33.0
END DESCRIPTION:
XS GIS Cut Line= 3
      1628705.00      7004338.00      1630505.00      7002838.00
      1630104.99      7001637.98
#Sta/Elev= 30
  2661.5 1545.07  3478.3 1526.38  3854.5 1521.41  4373.4 1516.39  4515.8 1515.53
  4860.3 1514.41  4919.3 1513.59  4960.4 1509.69  4960.9 1509.19  4977.2 1509.69
  4990.9 1511.13  5001.3 1514.79  5040.9 1515.33  5611.5 1524.16  5632.9 1524.46
  5710.8 1525.46  5775.1 1522.81  5816.2 1521.98  5847.8 1522.30  5868.9 1524.13
  5900.5 1523.27  5921.6 1524.06  5932.2 1525.26  5942.7 1530.25  5963.8 1530.85
  5974.3 1532.87  6069.2 1540.39  6132.4 1551.92  6147.2 1552.69  6269.5 1556.63
#Mann=11,-1,0
  2661.5   0.035       0  4373.4    0.07       0  4515.8   0.035       0
  4860.3    0.16       0  4960.4    0.07       0  4977.2    0.16       0
  5040.9   0.035       0  5611.5    0.07       0  5632.9   0.035       0
  5775.1    0.07       0  6147.2   0.035       0
Bank Sta=4960.4,4977.2
Exp/Cntr=0.3,0.1

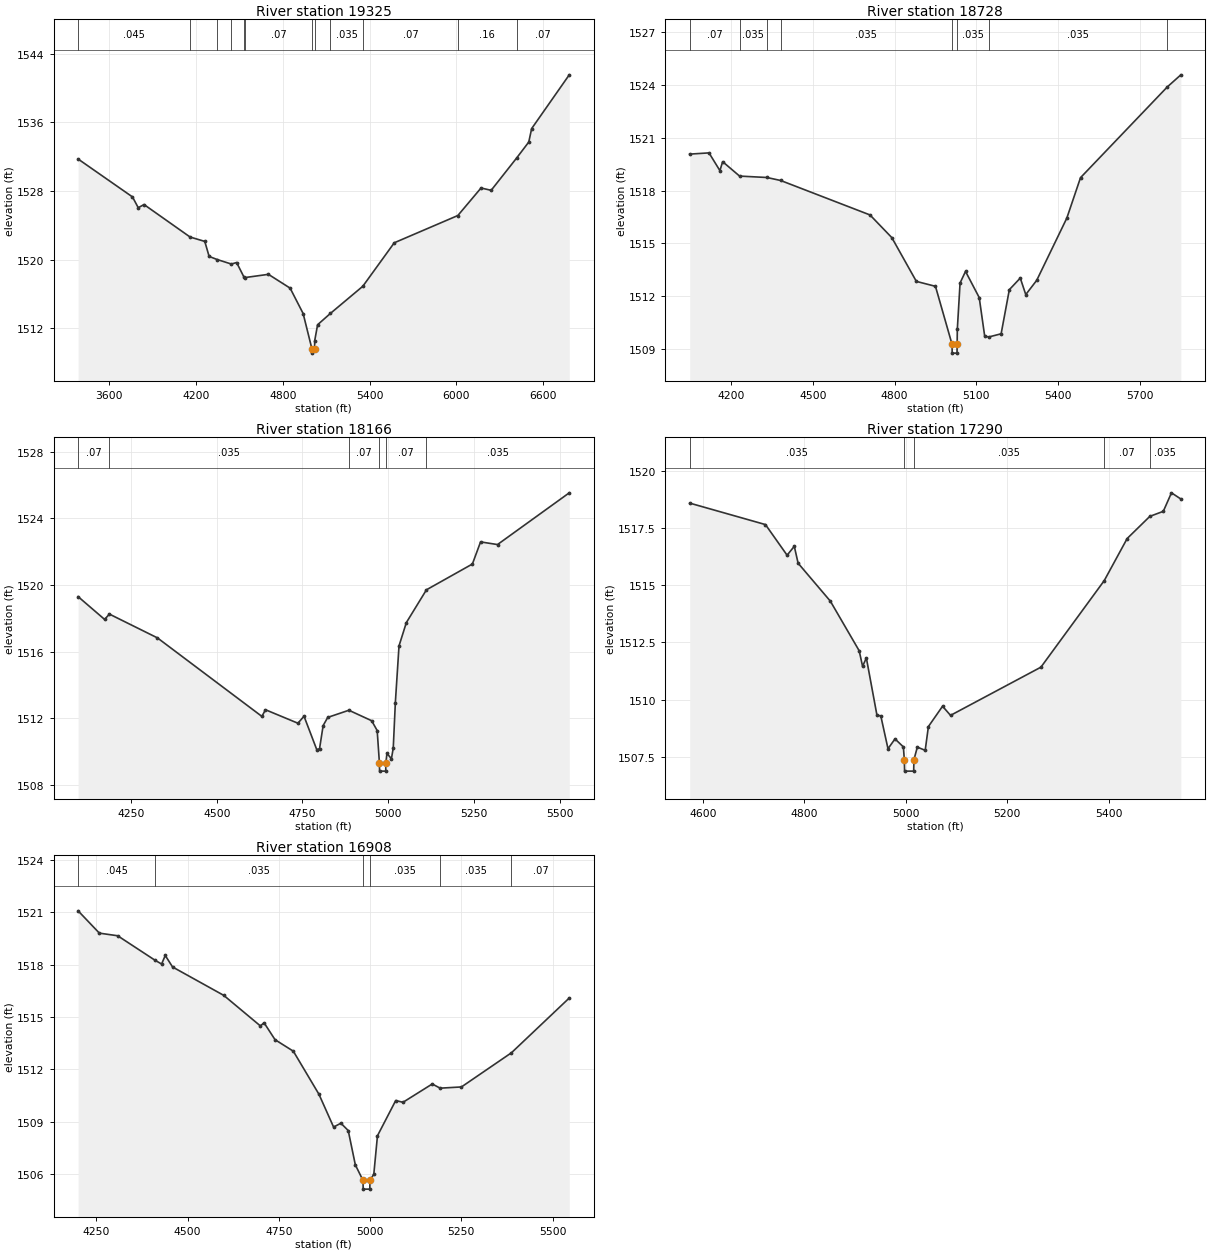
Type RM Length L Ch R = 1,19325,597,597,597
BEGIN DESCRIPTION:
Pinto Creek 32.0
END DESCRIPTION:
XS GIS Cut Line= 3
      1631090.52      7004653.91      1631055.10      7003038.10
      1631012.40      7001258.01
#Sta/Elev= 30
  3383.8 1531.74  3759.8 1527.32  3799.8 1526.06  3839.8 1526.43  4158.4 1522.64
  4259.9 1522.13  4289.9 1520.38  4345.1 1520.02  4443.9 1519.49  4480.0 1519.67
  4531.8 1517.94  4541.0 1517.92  4700.0 1518.29  4850.1 1516.68  4940.1 1513.72
  5000.8 1509.60  5001.3 1509.10  5019.4 1509.60  5020.1 1510.55  5040.1 1512.41
  5128.6 1513.73  5352.9 1516.90  5570.3 1521.97  6010.1 1525.15  6170.4 1528.36
  6240.5 1528.09  6416.3 1531.85  6500.5 1533.72  6520.5 1535.29  6780.6 1541.56
#Mann=12,-1,0
  3383.8   0.045       0  4158.4    0.07       0  4345.1   0.035       0
  4443.9    0.07       0  4531.8   0.035       0  4541.0    0.07       0
  5000.8    0.07       0  5019.4    0.07       0  5128.6   0.035       0
  5352.9    0.07       0  6010.1    0.16       0  6416.3    0.07       0
Bank Sta=5000.8,5019.4
Exp/Cntr=0.3,0.1

Type RM Length L Ch R = 1,18728,562,562,562
BEGIN DESCRIPTION:
Mapping XS b0bdcfc5
END DESCRIPTION:
XS GIS Cut Line= 3
      1631583.87      7003788.79      1631566.50      7002836.09
      1631497.20      7001991.39
#Sta/Elev= 30
  4049.0 1520.08  4119.8 1520.15  4159.8 1519.14  4169.8 1519.65  4231.9 1518.83
  4332.0 1518.75  4382.4 1518.58  4709.9 1516.62  4789.9 1515.33  4879.9 1512.84
  4949.9 1512.56  5010.7 1509.26  5011.2 1508.76  5028.9 1508.76  5029.4 1509.26
  5030.0 1510.11  5040.1 1512.75  5060.1 1513.41  5110.3 1511.92  5130.4 1509.72
  5145.7 1509.68  5190.6 1509.86  5220.7 1512.37  5260.8 1513.03  5280.9 1512.09
  5321.0 1512.90  5431.4 1516.44  5481.6 1518.74  5799.6 1523.90  5849.4 1524.59
#Mann=8,-1,0
  4049.0    0.07       0  4231.9   0.035       0  4332.0    0.07       0
  4382.4   0.035       0  5010.7   0.035       0  5029.4   0.035       0
  5145.7   0.035       0  5799.6    0.16       0
Bank Sta=5010.7,5029.4
Exp/Cntr=0.3,0.1

Type RM Length L Ch R = 1,18166,876,876,876
BEGIN DESCRIPTION:
Mapping XS b8b53651
END DESCRIPTION:
XS GIS Cut Line= 3
      1631796.73      7003668.14      1632074.50      7002808.78
      1632263.29      7002314.01
#Sta/Elev= 30
  4095.6 1519.30  4172.9 1517.93  4186.9 1518.25  4327.0 1516.82  4631.7 1512.10
  4642.2 1512.50  4736.8 1511.69  4754.6 1512.11  4791.8 1510.10  4799.9 1510.16
  4810.4 1511.55  4823.8 1512.04  4885.5 1512.47  4951.9 1511.84  4968.0 1511.25
  4974.5 1509.31  4975.0 1508.81  4992.9 1508.81  4993.4 1509.31  4996.5 1509.88
  5009.5 1509.55  5014.9 1510.20  5021.0 1512.93  5031.7 1516.34  5053.1 1517.74
  5111.7 1519.71  5245.7 1521.26  5269.6 1522.59  5319.0 1522.43  5528.3 1525.54
#Mann=6,-1,0
  4095.6    0.07       0  4186.9   0.035       0  4885.5    0.07       0
  4974.5    0.07       0  4993.4    0.07       0  5111.7   0.035       0
Bank Sta=4974.5,4993.4
Exp/Cntr=0.3,0.1

Type RM Length L Ch R = 1,17290,382,382,382
BEGIN DESCRIPTION:
Mapping XS 0b43fe43
END DESCRIPTION:
XS GIS Cut Line= 3
      1631913.94      7003848.24      1632196.03      7003535.78
      1632458.59      7003056.21
#Sta/Elev= 30
  4574.1 1518.60  4723.4 1517.66  4766.0 1516.32  4780.2 1516.71  4787.7 1515.97
  4851.2 1514.31  4908.0 1512.14  4914.7 1511.46  4922.2 1511.82  4943.1 1509.31
  4950.6 1509.29  4964.8 1507.85  4978.6 1508.28  4995.1 1507.93  4997.0 1507.37
  4997.5 1506.87  5015.4 1506.87  5015.9 1507.37  5022.6 1507.92  5038.1 1507.78
  5044.4 1508.82  5072.3 1509.71  5088.0 1509.31  5266.1 1511.42  5390.9 1515.21
  5436.0 1517.05  5480.7 1518.02  5507.2 1518.24  5523.3 1519.05  5541.8 1518.78
#Mann=5,-1,0
  4574.1   0.035       0  4997.0   0.035       0  5015.9   0.035       0
  5390.9    0.07       0  5480.7   0.035       0
Bank Sta=4997,5015.9
Exp/Cntr=0.3,0.1

Type RM Length L Ch R = 1,16908,1041,1041,1041
BEGIN DESCRIPTION:
Mapping XS 8f8833cf
END DESCRIPTION:
XS GIS Cut Line= 3
      1632415.21      7004536.16      1632472.50      7003739.26
      1632485.52      7003192.67
#Sta/Elev= 30
  4200.2 1521.09  4258.5 1519.81  4308.6 1519.66  4411.4 1518.25  4429.0 1518.04
  4439.0 1518.53  4459.0 1517.87  4599.4 1516.24  4699.6 1514.49  4709.7 1514.67
  4739.8 1513.70  4789.9 1513.04  4860.1 1510.57  4900.2 1508.69  4920.2 1508.91
  4940.3 1508.49  4959.8 1506.52  4980.8 1505.63  4981.3 1505.13  4999.4 1505.13
  4999.9 1505.63  5010.4 1505.99  5020.4 1508.19  5070.4 1510.21  5090.4 1510.11
  5170.5 1511.16  5192.1 1510.92  5250.5 1510.99  5387.5 1512.95  5545.9 1516.09
#Mann=6,-1,0
  4200.2   0.045       0  4411.4   0.035       0  4980.8    0.07       0
  4999.9   0.035       0  5192.1   0.035       0  5387.5    0.07       0
Bank Sta=4980.8,4999.9
Exp/Cntr=0.3,0.1