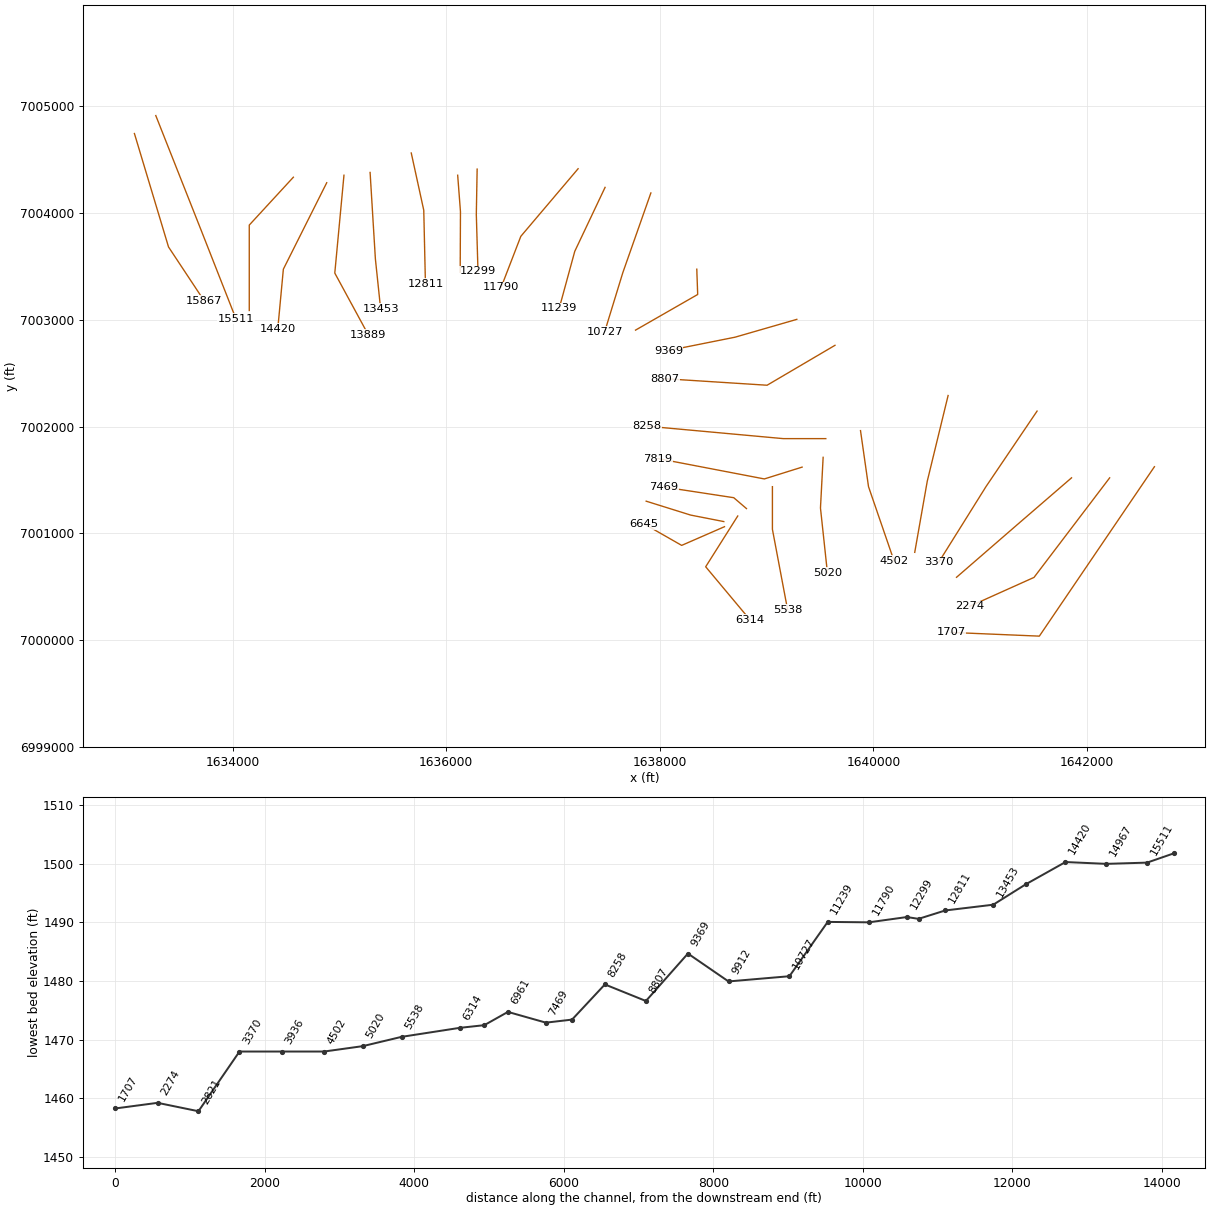
HEC-RAS study Pinto Creek.prj: Pinto Creek Base Level Engineering

--- Pinto Creek.g01 (geometry) --- (continued)

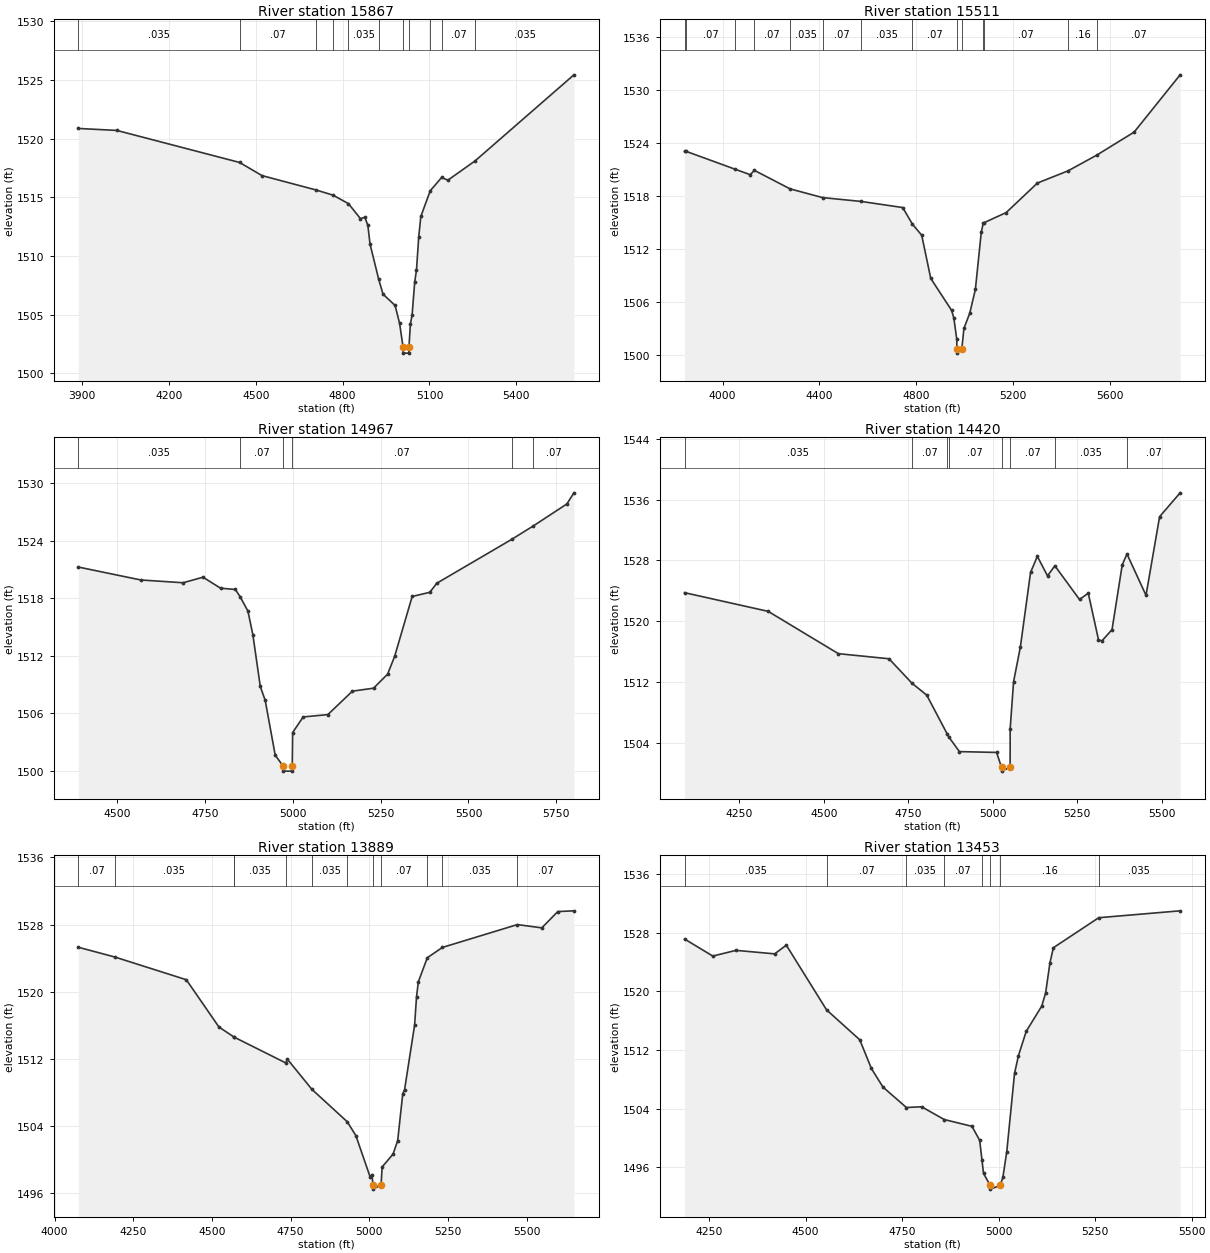
Type RM Length L Ch R = 1,15867,356,356,356
BEGIN DESCRIPTION:
Mapping XS 416331af
END DESCRIPTION:
XS GIS Cut Line= 3
      1633079.35      7004745.53      1633398.79      7003683.04
      1633731.08      7003181.14
#Sta/Elev= 30
  3887.4 1520.88  4020.6 1520.71  4444.4 1517.98  4521.8 1516.86  4707.7 1515.64
  4766.5 1515.20  4820.3 1514.47  4861.7 1513.19  4876.8 1513.31  4887.3 1512.61
  4894.7 1511.03  4924.6 1508.03  4939.5 1506.76  4981.3 1505.79  4996.9 1504.26
  5008.9 1502.23  5009.4 1501.73  5028.7 1501.73  5029.2 1502.23  5034.1 1504.21
  5040.1 1505.00  5049.1 1507.82  5055.1 1508.79  5062.9 1511.62  5070.2 1513.38
  5102.7 1515.57  5142.0 1516.70  5163.5 1516.47  5257.3 1518.11  5598.8 1525.45
#Mann=11,-1,0
  3887.4   0.035       0  4444.4    0.07       0  4707.7   0.035       0
  4766.5    0.07       0  4820.3   0.035       0  4924.6    0.07       0
  5008.9    0.07       0  5029.2    0.07       0  5102.7    0.16       0
  5142.0    0.07       0  5257.3   0.035       0
Bank Sta=5008.9,5029.2
Exp/Cntr=0.3,0.1

Type RM Length L Ch R = 1,15511,544,544,544
BEGIN DESCRIPTION:
Pinto Creek 25.0
END DESCRIPTION:
XS GIS Cut Line= 3
      1633279.54      7004913.67      1633705.00      7003838.00
      1634030.75      7003009.38
#Sta/Elev= 30
  3843.0 1523.05  3848.3 1523.07  4052.8 1521.02  4114.3 1520.41  4131.6 1520.90
  4278.9 1518.80  4412.9 1517.81  4573.4 1517.37  4744.2 1516.68  4784.6 1514.78
  4822.7 1513.54  4860.0 1508.64  4946.0 1505.02  4955.2 1504.17  4967.5 1501.73
  4968.1 1500.66  4968.6 1500.16  4988.4 1500.66  4997.1 1502.96  5021.2 1504.70
  5044.4 1507.39  5068.8 1513.90  5076.8 1514.89  5078.6 1514.94  5171.7 1516.11
  5300.6 1519.46  5426.9 1520.84  5545.8 1522.63  5700.1 1525.24  5890.1 1531.74
#Mann=14,-1,0
  3843.0   0.035       0  3848.3    0.07       0  4052.8   0.035       0
  4131.6    0.07       0  4278.9   0.035       0  4412.9    0.07       0
  4573.4   0.035       0  4784.6    0.07       0  4968.1    0.07       0
  4988.4    0.07       0  5076.8    0.16       0  5078.6    0.07       0
  5426.9    0.16       0  5545.8    0.07       0
Bank Sta=4968.1,4988.4
Exp/Cntr=0.3,0.1

Type RM Length L Ch R = 1,14967,547,547,547
BEGIN DESCRIPTION:
Pinto Creek 24.0
END DESCRIPTION:
XS GIS Cut Line= 3
      1634568.05      7004336.37      1634155.00      7003888.00
      1634155.00      7003088.03
#Sta/Elev= 30
  4390.4 1521.26  4568.2 1519.91  4688.4 1519.62  4745.1 1520.20  4795.0 1519.05
  4837.0 1518.92  4850.3 1518.18  4872.7 1516.67  4886.9 1514.19  4907.9 1508.80
  4922.0 1507.33  4950.4 1501.62  4973.4 1500.45  4973.9 1499.95  4998.4 1499.95
  4998.9 1500.45  5000.0 1503.98  5030.0 1505.61  5100.0 1505.85  5170.0 1508.30
  5230.0 1508.61  5270.0 1510.07  5290.0 1511.92  5340.0 1518.19  5390.0 1518.62
  5410.0 1519.57  5623.0 1524.15  5684.8 1525.56  5780.0 1527.85  5800.0 1529.01
#Mann=6,-1,0
  4390.4   0.035       0  4850.3    0.07       0  4973.4    0.07       0
  4998.9    0.07       0  5623.0   0.035       0  5684.8    0.07       0
Bank Sta=4973.4,4998.9
Exp/Cntr=0.3,0.1

Type RM Length L Ch R = 1,14420,531,531,531
BEGIN DESCRIPTION:
Mapping XS 67ee153f
END DESCRIPTION:
XS GIS Cut Line= 3
      1634880.55      7004284.71      1634474.31      7003474.84
      1634422.22      7002917.52
#Sta/Elev= 30
  4088.2 1523.75  4335.5 1521.29  4543.2 1515.72  4692.9 1515.05  4761.2 1511.82
  4804.6 1510.26  4864.9 1505.17  4870.1 1504.74  4901.2 1502.83  5011.2 1502.72
  5025.7 1500.76  5026.2 1500.26  5051.2 1500.76  5051.3 1505.81  5061.4 1512.03
  5081.5 1516.59  5111.6 1526.41  5131.7 1528.53  5161.8 1525.96  5183.5 1527.29
  5256.4 1522.85  5282.3 1523.68  5312.5 1517.57  5322.5 1517.39  5352.6 1518.89
  5382.8 1527.41  5396.8 1528.84  5453.1 1523.40  5493.3 1533.75  5554.0 1536.89
#Mann=8,-1,0
  4088.2   0.035       0  4761.2    0.07       0  4864.9   0.035       0
  4870.1    0.07       0  5025.7    0.07       0  5051.2    0.07       0
  5183.5   0.035       0  5396.8    0.07       0
Bank Sta=5025.7,5051.2
Exp/Cntr=0.3,0.1

Type RM Length L Ch R = 1,13889,436,436,436
BEGIN DESCRIPTION:
Mapping XS 66f5adc1
END DESCRIPTION:
XS GIS Cut Line= 3
      1635042.02      7004355.02      1634956.08      7003438.38
      1635268.56      7002862.90
#Sta/Elev= 30
  4075.2 1525.29  4190.9 1524.13  4418.5 1521.42  4522.2 1515.79  4569.3 1514.61
  4569.5 1514.60  4734.5 1511.51  4739.9 1511.95  4818.0 1508.35  4929.8 1504.51
  4957.5 1502.85  5003.0 1497.91  5008.7 1498.21  5012.0 1496.97  5012.5 1496.47
  5037.7 1496.97  5041.0 1499.11  5075.9 1500.65  5090.5 1502.26  5106.6 1507.84
  5112.3 1508.30  5144.2 1516.00  5150.3 1519.35  5156.0 1521.16  5184.6 1524.04
  5232.7 1525.27  5470.9 1527.99  5548.6 1527.60  5599.4 1529.54  5650.7 1529.63
#Mann=12,-1,0
  4075.2    0.07       0  4190.9   0.035       0  4569.3    0.07       0
  4569.5   0.035       0  4734.5    0.07       0  4818.0   0.035       0
  4929.8    0.07       0  5012.0    0.07       0  5037.7    0.07       0
  5184.6    0.16       0  5232.7   0.035       0  5470.9    0.07       0
Bank Sta=5012,5037.7
Exp/Cntr=0.3,0.1

Type RM Length L Ch R = 1,13453,642,642,642
BEGIN DESCRIPTION:
Mapping XS f50e2bd9
END DESCRIPTION:
XS GIS Cut Line= 3
      1635286.81      7004381.07      1635336.29      7003571.19
      1635385.60      7003101.46
#Sta/Elev= 30
  4186.5 1527.16  4259.7 1524.83  4319.8 1525.61  4420.0 1525.13  4450.1 1526.32
  4554.4 1517.48  4640.4 1513.39  4670.5 1509.47  4700.5 1506.93  4761.2 1504.14
  4800.7 1504.24  4859.1 1502.50  4931.0 1501.57  4951.0 1499.65  4957.0 1496.94
  4961.0 1495.14  4978.2 1493.49  4978.7 1492.99  5003.9 1493.49  5011.2 1494.62
  5021.2 1498.13  5041.3 1508.80  5051.4 1511.22  5071.5 1514.54  5111.7 1517.99
  5121.8 1519.79  5133.0 1523.91  5141.9 1525.97  5259.4 1530.07  5470.2 1531.01
#Mann=8,-1,0
  4186.5   0.035       0  4554.4    0.07       0  4761.2   0.035       0
  4859.1    0.07       0  4957.0    0.16       0  4978.2    0.07       0
  5003.9    0.16       0  5259.4   0.035       0
Bank Sta=4978.2,5003.9
Exp/Cntr=0.3,0.1

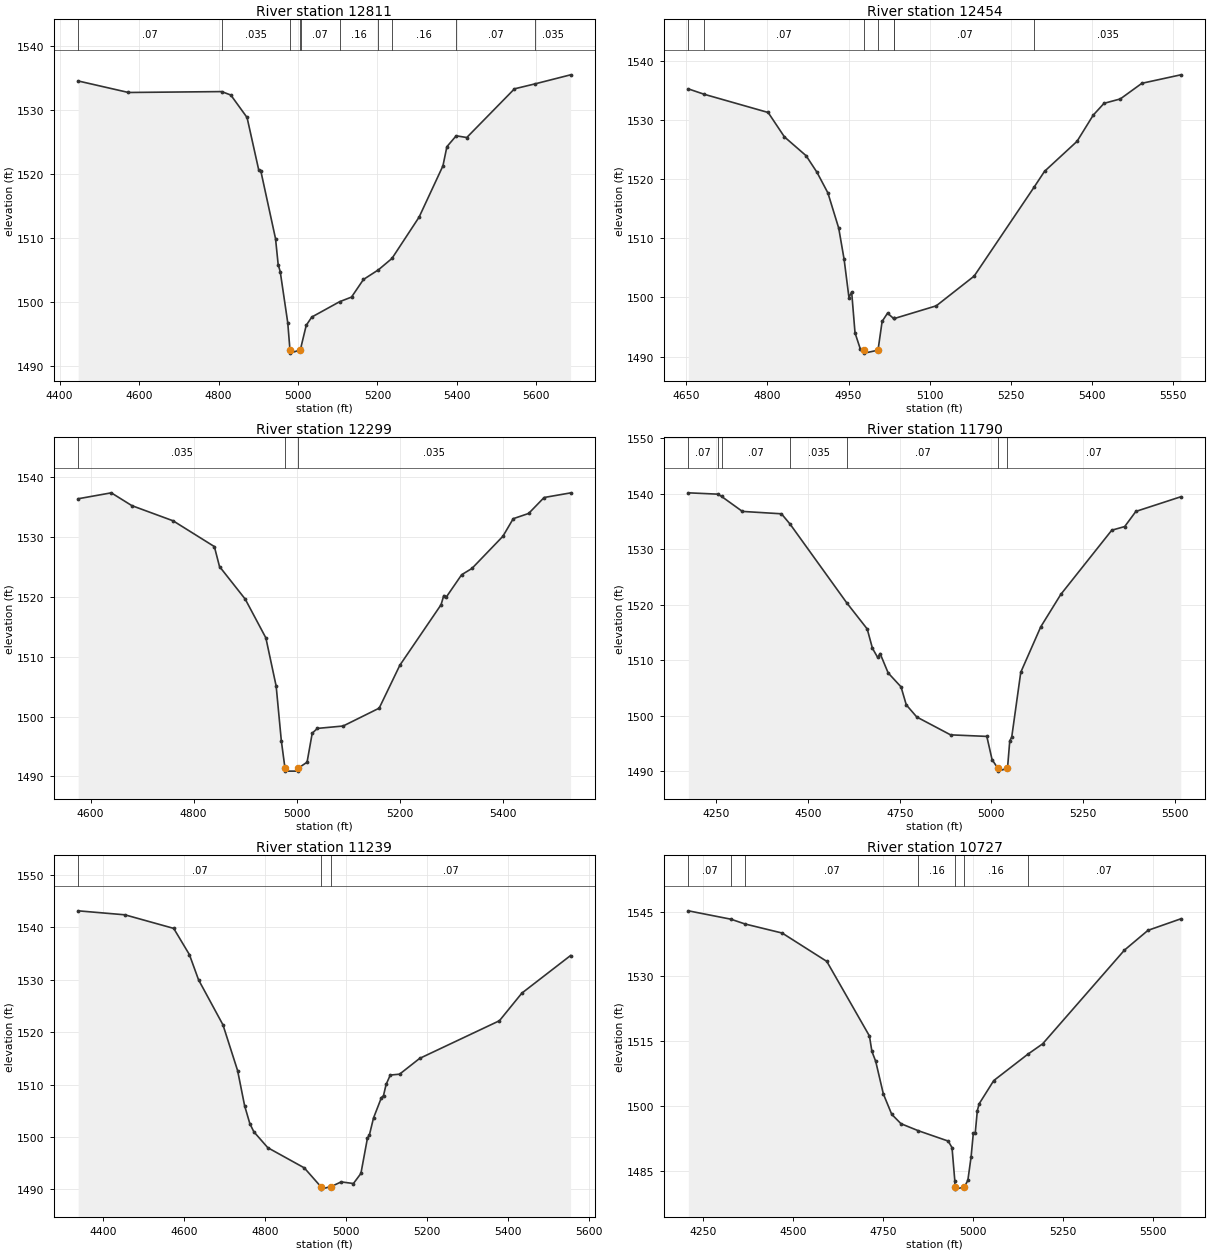
Type RM Length L Ch R = 1,12811,357,357,357
BEGIN DESCRIPTION:
Mapping XS 492bb513
END DESCRIPTION:
XS GIS Cut Line= 3
      1635672.23      7004563.35      1635789.41      7004026.92
      1635805.04      7003336.78
#Sta/Elev= 30
  4446.7 1534.55  4573.3 1532.75  4808.0 1532.89  4830.9 1532.35  4871.8 1528.84
  4901.1 1520.66  4906.2 1520.55  4943.5 1509.89  4950.1 1505.86  4955.3 1504.74
  4974.2 1496.77  4979.8 1492.51  4980.3 1492.01  5005.6 1492.51  5007.0 1492.81
  5020.7 1496.35  5034.7 1497.65  5104.8 1500.05  5134.7 1500.77  5164.7 1503.52
  5202.6 1505.04  5236.5 1506.81  5304.8 1513.27  5364.8 1521.28  5374.8 1524.28
  5398.2 1525.98  5424.8 1525.71  5544.8 1533.32  5596.2 1534.09  5686.1 1535.51
#Mann=10,-1,0
  4446.7    0.07       0  4808.0   0.035       0  4979.8   0.035       0
  5005.6   0.035       0  5007.0    0.07       0  5104.8    0.16       0
  5202.6    0.07       0  5236.5    0.16       0  5398.2    0.07       0
  5596.2   0.035       0
Bank Sta=4979.8,5005.6
Exp/Cntr=0.3,0.1

Type RM Length L Ch R = 1,12454,155,155,155
BEGIN DESCRIPTION:
Mapping XS a04c9469
END DESCRIPTION:
XS GIS Cut Line= 3
      1636107.13      7004355.00      1636133.16      7004013.90
      1636130.56      7003446.20
#Sta/Elev= 30
  4654.0 1535.28  4683.6 1534.36  4801.4 1531.29  4831.5 1527.16  4871.6 1523.97
  4891.7 1521.16  4911.8 1517.68  4931.8 1511.72  4941.8 1506.42  4950.7 1499.98
  4955.7 1500.93  4961.9 1494.01  4971.9 1491.22  4978.6 1491.08  4979.1 1490.58
  5004.4 1491.08  5012.0 1495.95  5022.0 1497.34  5033.2 1496.44  5034.7 1496.44
  5112.0 1498.58  5182.0 1503.61  5293.3 1518.73  5312.0 1521.33  5372.0 1526.40
  5402.0 1530.84  5422.0 1532.84  5452.0 1533.58  5492.0 1536.23  5563.8 1537.66
#Mann=7,-1,0
  4654.0   0.035       0  4683.6    0.07       0  4978.6    0.07       0
  5004.4    0.07       0  5033.2    0.16       0  5034.7    0.07       0
  5293.3   0.035       0
Bank Sta=4978.6,5004.4
Exp/Cntr=0.3,0.1

Type RM Length L Ch R = 1,12299,509,509,509
BEGIN DESCRIPTION:
Mapping XS 6e287f66
END DESCRIPTION:
XS GIS Cut Line= 3
      1636289.41      7004412.31      1636281.60      7003987.86
      1636297.23      7003456.61
#Sta/Elev= 30
  4575.9 1536.35  4640.2 1537.34  4680.2 1535.20  4760.2 1532.67  4840.3 1528.37
  4850.3 1525.04  4900.3 1519.59  4940.3 1513.13  4960.3 1505.08  4970.3 1495.98
  4977.4 1491.39  4977.9 1490.89  5002.7 1490.89  5003.2 1491.39  5020.3 1492.38
  5030.3 1497.22  5040.3 1498.02  5090.3 1498.42  5160.3 1501.40  5200.4 1508.56
  5280.4 1518.66  5285.7 1520.20  5290.7 1519.96  5320.4 1523.67  5340.4 1524.72
  5400.5 1530.09  5420.5 1533.02  5450.5 1533.90  5480.5 1536.56  5531.9 1537.33
#Mann=3,-1,0
  4575.9   0.035       0  4977.4   0.035       0  5003.2   0.035       0
Bank Sta=4977.4,5003.2
Exp/Cntr=0.3,0.1

Type RM Length L Ch R = 1,11790,551,551,551
BEGIN DESCRIPTION:
Mapping XS a297775a
END DESCRIPTION:
XS GIS Cut Line= 3
      1637234.96      7004415.69      1636698.53      7003782.91
      1636513.62      7003303.71
#Sta/Elev= 30
  4173.4 1540.16  4253.8 1539.92  4263.9 1539.51  4320.7 1536.81  4427.3 1536.38
  4451.3 1534.48  4605.5 1520.32  4661.2 1515.62  4675.5 1512.14  4689.8 1510.48
  4696.4 1511.19  4718.4 1507.69  4753.5 1505.18  4767.8 1501.94  4796.4 1499.75
  4888.6 1496.53  4987.5 1496.25  5001.8 1492.07  5017.7 1490.49  5018.2 1489.99
  5043.9 1490.49  5050.1 1495.46  5055.4 1496.10  5080.1 1507.81  5134.6 1516.00
  5189.2 1521.84  5328.3 1533.42  5363.6 1534.08  5394.1 1536.81  5516.6 1539.45
#Mann=7,-1,0
  4173.4    0.07       0  4253.8    0.16       0  4263.9    0.07       0
  4451.3   0.035       0  4605.5    0.07       0  5017.7    0.07       0
  5043.9    0.07       0
Bank Sta=5017.7,5043.9
Exp/Cntr=0.3,0.1

Type RM Length L Ch R = 1,11239,512,512,512
BEGIN DESCRIPTION:
Mapping XS 3998e028
END DESCRIPTION:
XS GIS Cut Line= 3
      1637487.60      7004241.26      1637203.74      7003642.29
      1637057.89      7003108.38
#Sta/Elev= 30
  4338.4 1543.13  4453.9 1542.37  4574.4 1539.78  4613.1 1534.79  4635.8 1529.97
  4696.1 1521.38  4732.3 1512.64  4749.5 1505.98  4762.5 1502.54  4772.3 1501.00
  4806.8 1497.96  4897.0 1494.11  4937.5 1490.56  4938.0 1490.06  4963.7 1490.56
  4988.0 1491.44  5018.3 1491.13  5036.8 1493.05  5052.8 1499.73  5058.0 1500.47
  5067.9 1503.62  5087.4 1507.50  5092.6 1507.90  5099.0 1510.02  5109.3 1511.81
  5132.3 1511.98  5181.9 1514.99  5378.9 1522.17  5434.4 1527.44  5554.7 1534.61
#Mann=3,-1,0
  4338.4    0.07       0  4937.5    0.07       0  4963.7    0.07       0
Bank Sta=4937.5,4963.7
Exp/Cntr=0.3,0.1

Type RM Length L Ch R = 1,10727,815,815,815
BEGIN DESCRIPTION:
Mapping XS 72ccb3ea
END DESCRIPTION:
XS GIS Cut Line= 3
      1637916.49      7004188.89      1637653.48      7003441.50
      1637484.75      7002891.20
#Sta/Elev= 30
  4209.3 1545.16  4327.7 1543.22  4366.7 1542.12  4469.9 1540.02  4593.8 1533.47
  4712.3 1516.22  4719.1 1512.67  4729.7 1510.36  4750.9 1502.83  4774.2 1498.11
  4799.9 1495.94  4848.2 1494.31  4931.1 1491.92  4941.7 1490.40  4949.4 1482.80
  4949.8 1481.31  4950.3 1480.81  4976.0 1481.31  4985.7 1482.85  4994.7 1488.28
  5000.8 1493.69  5006.1 1493.69  5012.0 1498.96  5017.2 1500.56  5057.6 1505.91
  5152.2 1512.00  5193.5 1514.41  5420.6 1536.07  5486.1 1540.65  5577.2 1543.31
#Mann=7,-1,0
  4209.3    0.07       0  4327.7   0.035       0  4366.7    0.07       0
  4848.2    0.16       0  4949.8    0.07       0  4976.0    0.16       0
  5152.2    0.07       0
Bank Sta=4949.8,4976
Exp/Cntr=0.3,0.1

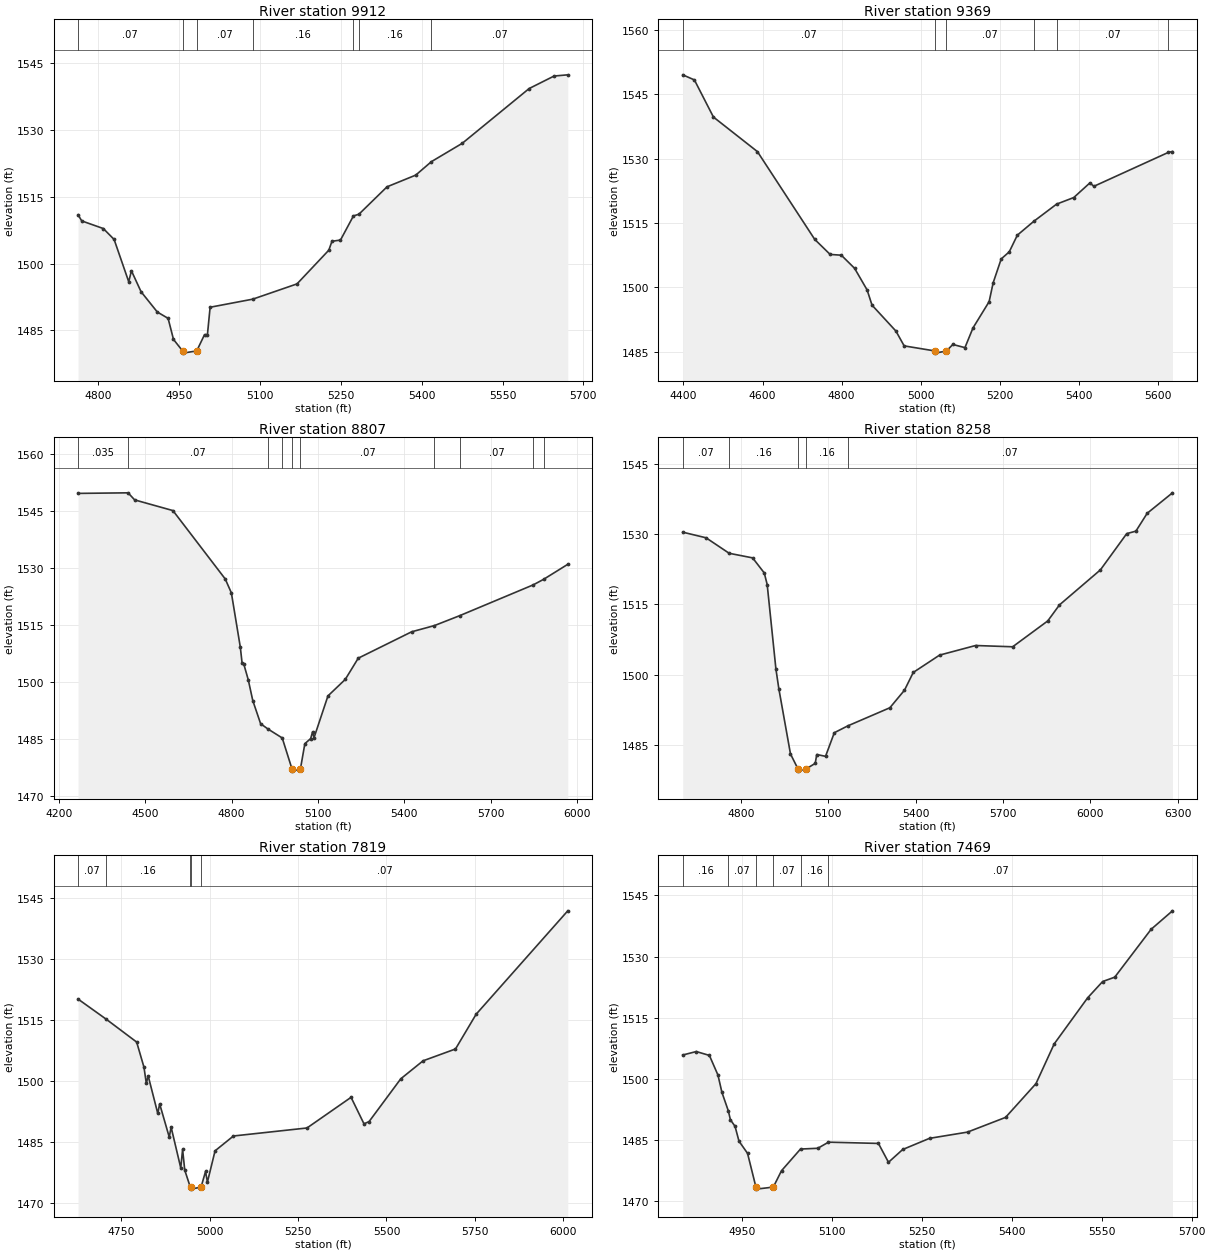
Type RM Length L Ch R = 1,9912,543,543,543
BEGIN DESCRIPTION:
Pinto Creek 15.0
END DESCRIPTION:
XS GIS Cut Line= 3
      1638346.59      7003474.87      1638355.00      7003238.00
      1637772.93      7002904.21
#Sta/Elev= 30
  4763.0 1510.92  4769.9 1509.54  4809.9 1507.83  4829.9 1505.39  4857.0 1495.91
  4862.0 1498.37  4879.9 1493.67  4910.0 1489.13  4930.0 1487.71  4940.0 1482.99
  4956.8 1480.42  4957.3 1479.92  4983.1 1480.42  4997.5 1484.05  5002.9 1484.05
  5007.9 1490.20  5086.9 1492.01  5169.0 1495.43  5228.0 1502.99  5233.8 1504.98
  5249.6 1505.25  5273.6 1510.66  5283.7 1511.03  5335.9 1517.18  5389.1 1519.80
  5418.2 1522.82  5475.4 1526.93  5599.4 1539.20  5645.6 1542.00  5671.0 1542.27
#Mann=7,-1,0
  4763.0    0.07       0  4956.8    0.07       0  4983.1    0.07       0
  5086.9    0.16       0  5273.6    0.07       0  5283.7    0.16       0
  5418.2    0.07       0
Bank Sta=4956.8,4983.1
Exp/Cntr=0.3,0.1

Type RM Length L Ch R = 1,9369,562,562,562
BEGIN DESCRIPTION:
Pinto Creek 14.0
END DESCRIPTION:
XS GIS Cut Line= 3
      1639283.35      7003004.90      1638705.00      7002838.00
      1638080.03      7002713.01
#Sta/Elev= 30
  4398.1 1549.58  4427.6 1548.39  4475.8 1539.73  4587.1 1531.67  4732.1 1511.20
  4771.1 1507.69  4799.4 1507.51  4833.0 1504.45  4864.7 1499.40  4877.1 1495.86
  4937.6 1489.81  4958.4 1486.36  5036.7 1485.17  5037.2 1484.67  5065.4 1485.17
  5081.6 1486.69  5112.2 1485.95  5132.6 1490.55  5173.4 1496.67  5183.6 1501.07
  5204.0 1506.64  5224.4 1508.30  5244.8 1512.18  5286.4 1515.41  5344.1 1519.42
  5387.6 1520.96  5428.4 1524.37  5438.6 1523.58  5627.0 1531.49  5637.4 1531.69
#Mann=6,-1,0
  4398.1    0.07       0  5036.7    0.07       0  5065.4    0.07       0
  5286.4   0.035       0  5344.1    0.07       0  5627.0   0.035       0
Bank Sta=5036.7,5065.4
Exp/Cntr=0.3,0.1

Type RM Length L Ch R = 1,8807,549,549,549
BEGIN DESCRIPTION:
Pinto Creek 13.0
END DESCRIPTION:
XS GIS Cut Line= 3
      1639640.98      7002761.85      1639005.00      7002388.00
      1638043.78      7002449.34
#Sta/Elev= 30
  4266.9 1549.63  4440.7 1549.78  4463.6 1547.92  4596.5 1545.11  4778.1 1527.13
  4799.5 1523.46  4830.6 1509.16  4836.7 1505.00  4842.5 1504.76  4858.1 1500.62
  4873.8 1495.15  4901.1 1489.05  4926.9 1487.65  4976.1 1485.31  5010.3 1477.09
  5010.8 1476.59  5039.1 1477.09  5054.7 1483.81  5074.8 1485.15  5081.5 1486.91
  5086.5 1485.37  5134.9 1496.37  5195.0 1500.71  5240.1 1506.29  5425.5 1513.23
  5504.4 1514.86  5592.0 1517.46  5847.7 1525.57  5883.8 1527.03  5967.8 1530.98
#Mann=10,-1,0
  4266.9   0.035       0  4440.7    0.07       0  4926.9    0.16       0
  4976.1    0.07       0  5010.3    0.07       0  5039.1    0.07       0
  5504.4   0.035       0  5592.0    0.07       0  5847.7   0.035       0
  5883.8    0.07       0
Bank Sta=5010.3,5039.1
Exp/Cntr=0.3,0.1

Type RM Length L Ch R = 1,8258,439,439,439
BEGIN DESCRIPTION:
Pinto Creek 12.0
END DESCRIPTION:
XS GIS Cut Line= 3
      1639554.98      7001888.00      1639155.00      7001888.00
      1637878.51      7002004.76
#Sta/Elev= 30
  4600.1 1530.43  4680.1 1529.23  4759.6 1525.92  4840.1 1524.94  4880.1 1521.72
  4890.1 1519.25  4920.1 1501.20  4930.1 1497.01  4970.1 1483.08  4995.6 1479.91
  4996.1 1479.41  5024.6 1479.91  5055.1 1481.07  5060.3 1482.96  5090.5 1482.57
  5120.6 1487.61  5167.2 1489.08  5311.4 1492.94  5361.6 1496.69  5391.7 1500.48
  5482.1 1504.18  5605.7 1506.23  5733.1 1505.96  5853.6 1511.48  5893.8 1514.90
  6034.4 1522.38  6124.8 1530.12  6156.3 1530.65  6195.0 1534.46  6281.9 1538.83
#Mann=5,-1,0
  4600.1    0.07       0  4759.6    0.16       0  4995.6    0.07       0
  5024.6    0.16       0  5167.2    0.07       0
Bank Sta=4995.6,5024.6
Exp/Cntr=0.3,0.1

Type RM Length L Ch R = 1,7819,350,350,350
BEGIN DESCRIPTION:
Mapping XS a5d5e551
END DESCRIPTION:
XS GIS Cut Line= 3
      1639333.00      7001621.05      1638979.24      7001510.36
      1637983.15      7001701.34
#Sta/Elev= 30
  4627.8 1520.17  4707.1 1515.24  4793.6 1509.59  4814.3 1503.40  4820.9 1499.43
  4826.1 1501.30  4853.3 1492.03  4858.6 1494.39  4885.8 1486.20  4891.0 1488.68
  4918.3 1478.64  4923.5 1483.17  4929.6 1478.08  4944.3 1474.17  4946.7 1473.92
  4947.2 1473.42  4975.7 1473.92  4988.4 1477.76  4993.7 1475.15  5015.3 1482.84
  5067.3 1486.49  5275.3 1488.46  5399.9 1496.00  5436.4 1489.48  5450.8 1490.03
  5540.5 1500.56  5603.5 1504.98  5695.2 1507.89  5753.6 1516.44  6012.7 1541.87
#Mann=5,-1,0
  4627.8    0.07       0  4707.1    0.16       0  4944.3    0.07       0
  4946.7    0.07       0  4975.7    0.07       0
Bank Sta=4946.7,4975.7
Exp/Cntr=0.3,0.1

Type RM Length L Ch R = 1,7469,508,508,508
BEGIN DESCRIPTION:
Mapping XS 597c8604
END DESCRIPTION:
XS GIS Cut Line= 3
      1638812.12      7001232.60      1638692.79      7001334.58
      1638039.74      7001434.38
#Sta/Elev= 30
  4850.4 1505.83  4873.0 1506.68  4894.9 1505.73  4909.2 1500.91  4915.8 1496.66
  4926.5 1492.12  4930.0 1489.92  4937.7 1488.33  4944.3 1484.68  4958.6 1481.68
  4972.6 1473.40  4973.1 1472.90  5001.6 1473.40  5015.3 1477.42  5047.0 1482.74
  5075.9 1482.93  5093.7 1484.43  5177.1 1484.12  5193.9 1479.49  5217.6 1482.63
  5262.4 1485.37  5325.8 1486.90  5389.3 1490.51  5440.1 1498.80  5470.5 1508.55
  5526.3 1519.86  5551.4 1523.87  5571.6 1524.94  5632.3 1536.69  5668.0 1541.23
#Mann=6,-1,0
  4850.4    0.16       0  4926.5    0.07       0  4972.6    0.07       0
  5001.6    0.07       0  5047.0    0.16       0  5093.7    0.07       0
Bank Sta=4972.6,5001.6
Exp/Cntr=0.3,0.1

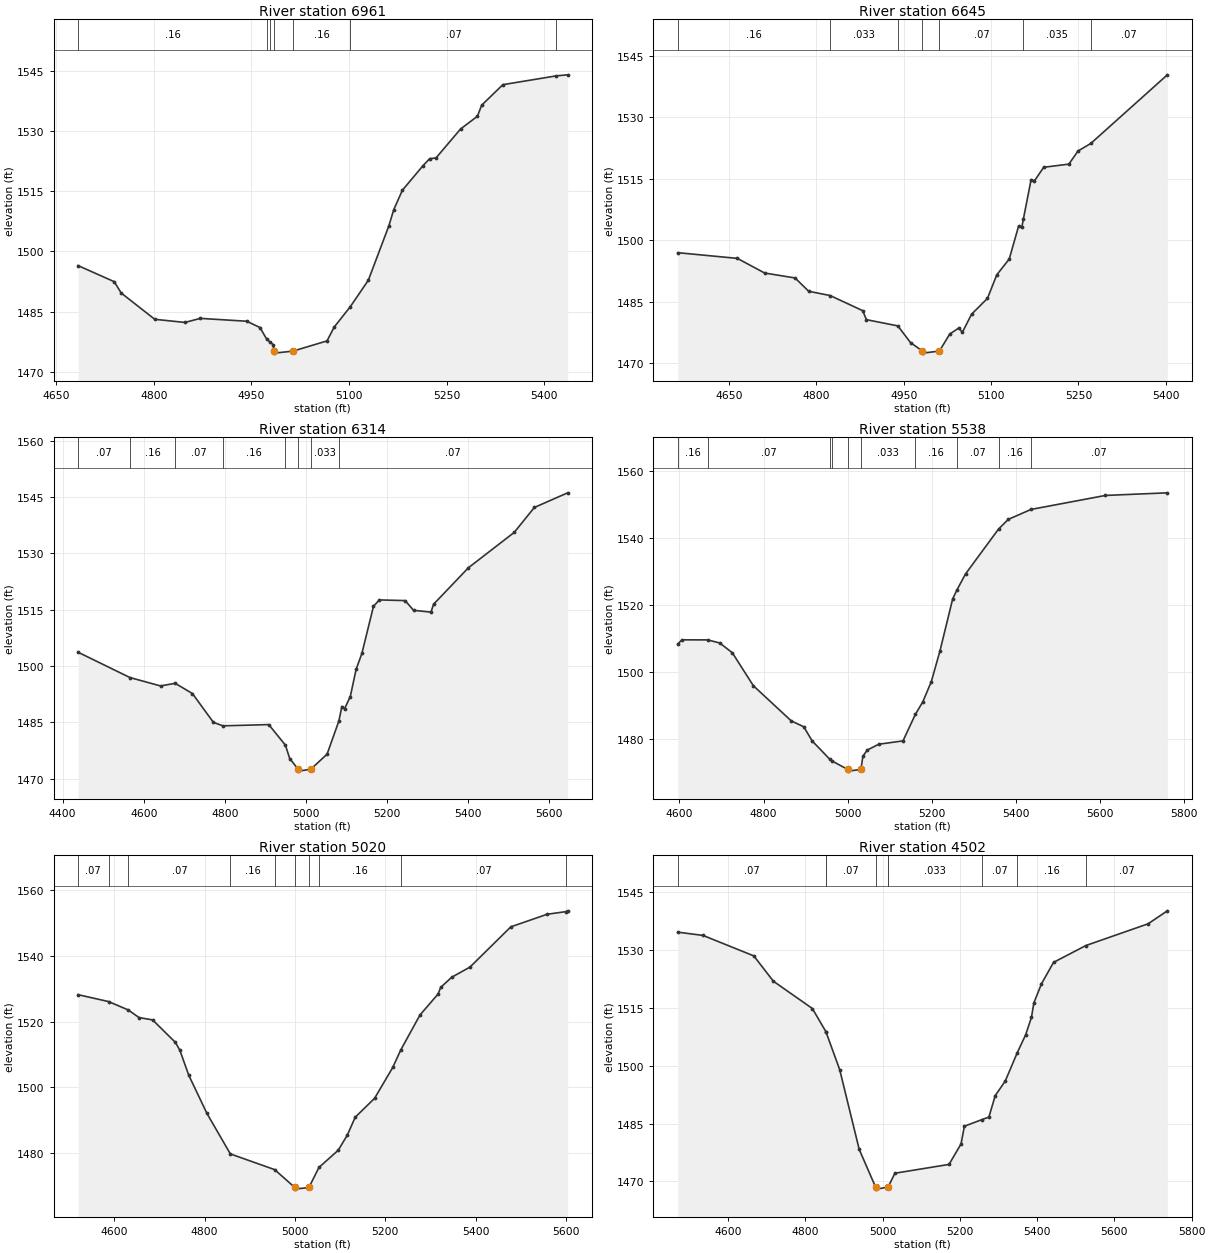
Type RM Length L Ch R = 1,6961,316,316,316
BEGIN DESCRIPTION:
Mapping XS 7d013062
END DESCRIPTION:
XS GIS Cut Line= 3
      1638599.52      7001111.05      1638289.14      7001171.82
      1637872.48      7001302.03
#Sta/Elev= 30
  4683.4 1496.50  4739.0 1492.50  4749.9 1489.66  4801.4 1483.14  4847.8 1482.36
  4871.4 1483.37  4942.8 1482.66  4963.1 1481.10  4973.7 1478.14  4979.3 1477.39
  4983.5 1476.83  4984.7 1475.23  4985.2 1474.73  5013.8 1475.23  5066.2 1477.77
  5077.3 1481.23  5101.9 1486.25  5129.7 1492.85  5161.2 1506.34  5168.8 1510.40
  5182.1 1515.24  5213.5 1521.29  5224.0 1523.08  5233.8 1523.27  5271.5 1530.46
  5297.4 1533.62  5304.0 1536.38  5336.5 1541.48  5419.0 1543.68  5436.2 1543.93
#Mann=7,-1,0
  4683.4    0.16       0  4973.7   0.033       0  4979.3    0.16       0
  4984.7    0.07       0  5013.8    0.16       0  5101.9    0.07       0
  5419.0   0.035       0
Bank Sta=4984.7,5013.8
Exp/Cntr=0.3,0.1

Type RM Length L Ch R = 1,6645,331,331,331
BEGIN DESCRIPTION:
Pinto Creek 11.0
END DESCRIPTION:
XS GIS Cut Line= 3
      1638605.99      7001063.00      1638205.00      7000888.00
      1637855.02      7001087.99
#Sta/Elev= 30
  4562.0 1496.99  4664.4 1495.60  4711.2 1492.03  4763.5 1490.82  4786.9 1487.57
  4823.7 1486.53  4879.5 1482.84  4886.0 1480.64  4939.9 1479.12  4961.7 1475.04
  4982.2 1472.97  4982.7 1472.47  5011.3 1472.97  5029.0 1477.13  5044.9 1478.63
  5050.6 1477.53  5066.5 1481.97  5093.8 1485.84  5109.7 1491.57  5131.2 1495.46
  5147.1 1503.42  5152.8 1503.17  5155.3 1505.12  5168.7 1514.83  5174.4 1514.51
  5190.3 1517.84  5233.5 1518.61  5249.3 1521.82  5271.2 1523.66  5402.6 1540.41
#Mann=7,-1,0
  4562.0    0.16       0  4823.7   0.033       0  4939.9    0.07       0
  4982.2    0.07       0  5011.3    0.07       0  5155.3   0.035       0
  5271.2    0.07       0
Bank Sta=4982.2,5011.3
Exp/Cntr=0.3,0.1

Type RM Length L Ch R = 1,6314,776,776,776
BEGIN DESCRIPTION:
Pinto Creek 10.0
END DESCRIPTION:
XS GIS Cut Line= 3
      1638730.02      7001163.04      1638429.90      7000687.76
      1638844.41      7000191.76
#Sta/Elev= 30
  4437.9 1503.67  4566.1 1496.92  4641.5 1494.69  4677.7 1495.39  4720.3 1492.66
  4772.1 1484.98  4795.5 1484.07  4908.6 1484.40  4949.9 1478.91  4960.3 1475.37
  4981.3 1472.51  4981.8 1472.01  5012.3 1472.51  5052.6 1476.53  5081.6 1485.33
  5089.1 1489.21  5095.6 1488.59  5109.9 1491.86  5124.2 1499.09  5138.5 1503.34
  5167.1 1515.89  5181.5 1517.59  5245.2 1517.41  5266.1 1514.82  5309.0 1514.34
  5315.5 1516.45  5401.4 1526.15  5514.6 1535.58  5564.1 1542.20  5646.4 1546.10
#Mann=8,-1,0
  4437.9    0.07       0  4566.1    0.16       0  4677.7    0.07       0
  4795.5    0.16       0  4949.9   0.033       0  4981.3   0.033       0
  5012.3   0.033       0  5081.6    0.07       0
Bank Sta=4981.3,5012.3
Exp/Cntr=0.3,0.1

Type RM Length L Ch R = 1,5538,518,518,518
BEGIN DESCRIPTION:
Pinto Creek 9.0
END DESCRIPTION:
XS GIS Cut Line= 3
      1639055.00      7001437.98      1639055.00      7001038.00
      1639196.95      7000286.06
#Sta/Elev= 30
  4595.8 1508.42  4605.8 1509.69  4667.0 1509.67  4695.8 1508.75  4725.8 1505.83
  4775.8 1495.99  4865.8 1485.51  4895.8 1483.72  4915.8 1479.49  4957.9 1474.00
  4963.5 1473.48  5000.6 1470.98  5001.1 1470.48  5031.7 1470.98  5036.5 1474.91
  5046.7 1476.76  5074.4 1478.52  5131.9 1479.51  5161.2 1487.40  5179.0 1491.16
  5199.3 1497.21  5219.7 1506.29  5250.2 1521.94  5260.3 1524.59  5280.7 1529.37
  5359.4 1542.79  5382.5 1545.66  5436.5 1548.63  5613.6 1552.81  5761.0 1553.59
#Mann=10,-1,0
  4595.8    0.16       0  4667.0    0.07       0  4957.9    0.16       0
  4963.5   0.033       0  5000.6   0.033       0  5031.7   0.033       0
  5161.2    0.16       0  5260.3    0.07       0  5359.4    0.16       0
  5436.5    0.07       0
Bank Sta=5000.6,5031.7
Exp/Cntr=0.3,0.1

Type RM Length L Ch R = 1,5020,518,518,518
BEGIN DESCRIPTION:
Pinto Creek 8.0
END DESCRIPTION:
XS GIS Cut Line= 3
      1639530.00      7001712.96      1639505.00      7001238.00
      1639569.98      7000632.80
#Sta/Elev= 30
  4519.6 1528.20  4587.2 1526.09  4631.1 1523.52  4654.7 1521.21  4684.8 1520.50
  4734.9 1513.69  4744.9 1511.33  4764.9 1503.60  4805.0 1492.00  4856.9 1479.64
  4955.0 1474.85  4999.7 1469.40  5000.2 1468.90  5030.9 1469.40  5053.1 1475.52
  5095.8 1480.75  5115.9 1485.37  5133.4 1490.82  5176.3 1496.59  5216.5 1506.00
  5234.4 1511.37  5276.8 1521.99  5317.1 1528.43  5322.6 1530.40  5347.2 1533.52
  5387.5 1536.60  5478.0 1548.88  5558.4 1552.71  5600.2 1553.52  5603.9 1553.76
#Mann=10,-1,0
  4519.6    0.07       0  4587.2    0.16       0  4631.1    0.07       0
  4856.9    0.16       0  4955.0   0.033       0  4999.7   0.033       0
  5030.9   0.033       0  5053.1    0.16       0  5234.4    0.07       0
  5600.2   0.035       0
Bank Sta=4999.7,5030.9
Exp/Cntr=0.3,0.1

Type RM Length L Ch R = 1,4502,566,566,566
BEGIN DESCRIPTION:
Pinto Creek 7.0
END DESCRIPTION:
XS GIS Cut Line= 3
      1639880.00      7001962.99      1639955.00      7001438.00
      1640194.67      7000741.29
#Sta/Elev= 30
  4470.0 1534.63  4535.6 1533.78  4667.0 1528.47  4717.5 1521.91  4818.5 1514.82
  4853.6 1508.80  4854.1 1508.65  4889.2 1498.97  4939.7 1478.28  4982.2 1468.48
  4982.7 1467.98  5013.4 1468.48  5014.3 1468.48  5032.0 1472.10  5172.1 1474.39
  5203.3 1479.72  5211.8 1484.29  5257.7 1486.03  5275.3 1486.67  5291.7 1492.24
  5317.6 1496.01  5348.9 1503.41  5370.4 1508.01  5385.4 1512.53  5391.6 1516.27
  5411.4 1521.25  5442.6 1526.79  5526.3 1531.16  5687.2 1536.79  5737.1 1540.16
#Mann=9,-1,0
  4470.0    0.07       0  4853.6   0.035       0  4854.1    0.07       0
  4982.2    0.07       0  5013.4    0.07       0  5014.3   0.033       0
  5257.7    0.07       0  5348.9    0.16       0  5526.3    0.07       0
Bank Sta=4982.2,5013.4
Exp/Cntr=0.3,0.1

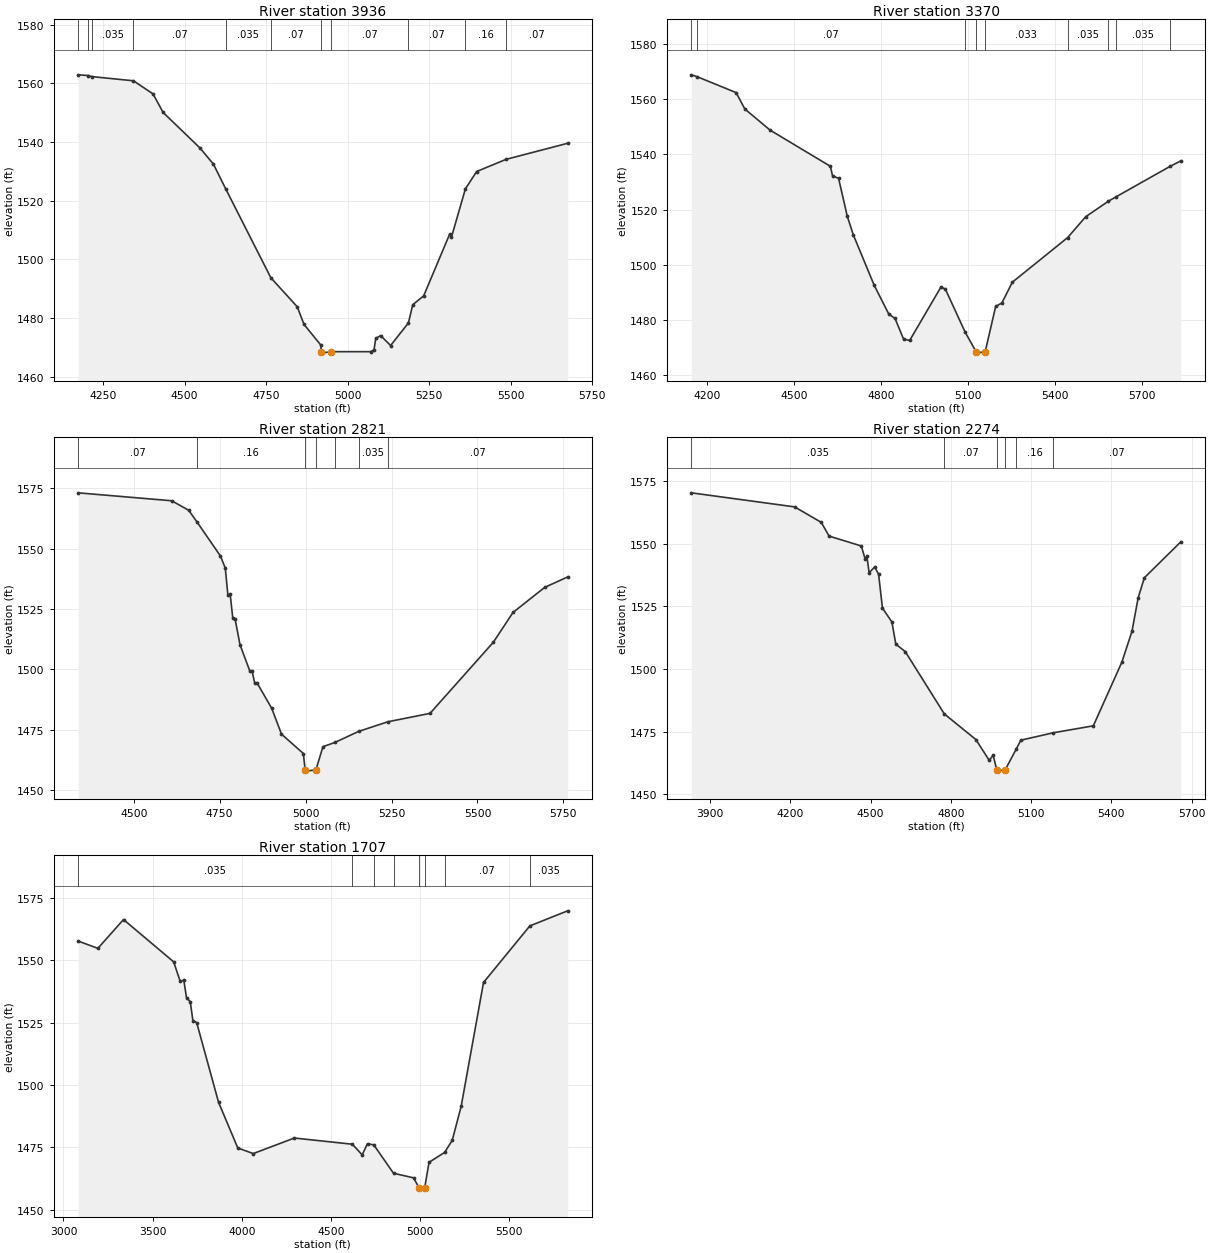
Type RM Length L Ch R = 1,3936,566,566,566
BEGIN DESCRIPTION:
Pinto Creek 6.0
END DESCRIPTION:
XS GIS Cut Line= 3
      1640700.46      7002291.68      1640505.00      7001488.00
      1640387.96      7000822.93
#Sta/Elev= 30
  4172.9 1562.88  4203.7 1562.65  4216.4 1562.26  4342.9 1560.85  4403.1 1556.37
  4434.0 1550.05  4547.2 1537.92  4588.4 1532.42  4626.0 1524.01  4764.5 1493.69
  4845.6 1483.78  4866.2 1477.80  4917.7 1470.75  4919.2 1468.48  4919.7 1467.98
  4950.4 1468.48  5071.1 1468.48  5081.2 1469.13  5086.4 1473.00  5101.5 1473.95
  5132.0 1470.58  5186.7 1478.28  5200.0 1484.50  5233.5 1487.51  5313.5 1508.62
  5318.6 1507.44  5361.5 1523.99  5396.0 1529.90  5486.1 1534.05  5675.3 1539.54
#Mann=11,-1,0
  4172.9   0.035       0  4203.7    0.07       0  4216.4   0.035       0
  4342.9    0.07       0  4626.0   0.035       0  4764.5    0.07       0
  4919.2   0.033       0  4950.4    0.07       0  5186.7    0.07       0
  5361.5    0.16       0  5486.1    0.07       0
Bank Sta=4919.2,4950.4
Exp/Cntr=0.3,0.1

Type RM Length L Ch R = 1,3370,549,549,549
BEGIN DESCRIPTION:
Pinto Creek 5.0
END DESCRIPTION:
XS GIS Cut Line= 3
      1641533.77      7002145.81      1641055.00      7001438.00
      1640611.94      7000729.21
#Sta/Elev= 30
  4145.0 1568.78  4165.5 1568.09  4299.9 1562.33  4329.8 1556.41  4416.7 1548.77
  4625.3 1535.64  4632.5 1532.25  4653.5 1531.27  4683.4 1517.60  4704.4 1510.81
  4776.3 1492.59  4827.2 1482.04  4848.2 1480.58  4878.1 1473.00  4899.1 1472.60
  5007.2 1491.98  5022.5 1491.09  5090.5 1475.56  5128.3 1468.48  5128.8 1467.98
  5159.6 1468.48  5195.9 1484.92  5217.1 1486.13  5253.6 1493.69  5444.2 1509.82
  5506.6 1517.38  5584.8 1522.99  5610.7 1524.55  5798.9 1535.68  5835.4 1537.63
#Mann=9,-1,0
  4145.0   0.035       0  4165.5    0.07       0  5090.5   0.033       0
  5128.3    0.07       0  5159.6   0.033       0  5444.2   0.035       0
  5584.8    0.07       0  5610.7   0.035       0  5798.9    0.07       0
Bank Sta=5128.3,5159.6
Exp/Cntr=0.3,0.1

Type RM Length L Ch R = 1,2821,547,547,547
BEGIN DESCRIPTION:
Pinto Creek 4.0
END DESCRIPTION:
XS GIS Cut Line= 3
      1641856.72      7001520.85      1641355.00      7001088.00
      1640779.29      7000589.16
#Sta/Elev= 30
  4337.9 1573.11  4610.5 1569.82  4659.9 1565.87  4685.1 1560.82  4752.1 1546.96
  4766.3 1541.94  4774.0 1530.59  4780.6 1531.01  4788.2 1521.10  4794.8 1520.80
  4809.1 1510.20  4837.6 1499.30  4844.2 1499.34  4851.9 1494.27  4858.5 1494.40
  4901.3 1483.86  4929.8 1473.13  4993.4 1465.11  4998.6 1458.31  4999.1 1457.81
  5029.9 1458.31  5050.4 1467.93  5085.0 1469.68  5154.3 1474.27  5239.3 1478.26
  5361.9 1481.74  5546.1 1511.20  5603.2 1523.53  5695.3 1533.92  5762.3 1538.27
#Mann=7,-1,0
  4337.9    0.07       0  4685.1    0.16       0  4998.6    0.07       0
  5029.9    0.16       0  5085.0    0.07       0  5154.3   0.035       0
  5239.3    0.07       0
Bank Sta=4998.6,5029.9
Exp/Cntr=0.3,0.1

Type RM Length L Ch R = 1,2274,567,567,567
BEGIN DESCRIPTION:
Pinto Creek 3.0
END DESCRIPTION:
XS GIS Cut Line= 3
      1642213.50      7001520.60      1641505.00      7000588.00
      1640903.55      7000317.71
#Sta/Elev= 30
  3829.4 1570.37  4215.6 1564.76  4315.4 1558.57  4344.5 1553.10  4465.1 1549.14
  4479.7 1543.81  4485.9 1545.12  4494.2 1538.44  4515.0 1540.76  4529.6 1537.91
  4544.1 1524.34  4579.5 1518.78  4594.0 1509.95  4629.4 1506.96  4775.6 1482.06
  4893.5 1471.85  4943.4 1463.51  4958.0 1465.60  4971.4 1459.74  4971.9 1459.24
  5002.8 1459.74  5043.9 1467.97  5061.3 1471.59  5183.0 1474.56  5332.5 1477.33
  5439.1 1502.74  5476.9 1515.05  5500.1 1528.44  5523.2 1536.45  5660.0 1550.85
#Mann=6,-1,0
  3829.4   0.035       0  4775.6    0.07       0  4971.4    0.07       0
  5002.8    0.07       0  5043.9    0.16       0  5183.0    0.07       0
Bank Sta=4971.4,5002.8
Exp/Cntr=0.3,0.1

Type RM Length L Ch R = 1,1707,0,0,0
BEGIN DESCRIPTION:
Pinto Creek 2.0
END DESCRIPTION:
XS GIS Cut Line= 3
      1642632.79      7001624.79      1641555.00      7000038.00
      1640728.25      7000072.85
#Sta/Elev= 30
  3081.7 1557.72  3193.1 1554.78  3336.8 1566.33  3618.2 1549.35  3654.1 1541.67
  3675.1 1541.98  3690.0 1534.96  3711.0 1533.43  3726.0 1525.78  3747.0 1525.04
  3869.7 1493.10  3977.5 1474.78  4064.3 1472.53  4294.8 1478.76  4620.1 1476.28
  4675.1 1472.01  4705.0 1476.50  4740.4 1475.99  4850.8 1464.64  4963.6 1462.80
  4994.2 1458.78  4994.7 1458.28  5025.6 1458.78  5050.0 1469.02  5137.8 1473.01
  5180.1 1477.84  5230.1 1491.40  5355.6 1541.11  5615.4 1563.78  5827.4 1569.82
#Mann=8,-1,0
  3081.7   0.035       0  4620.1    0.07       0  4740.4   0.035       0
  4850.8    0.16       0  4994.2    0.07       0  5025.6    0.16       0
  5137.8    0.07       0  5615.4   0.035       0
Bank Sta=4994.2,5025.6
Exp/Cntr=0.3,0.1

Chan Stop Cuts=-1