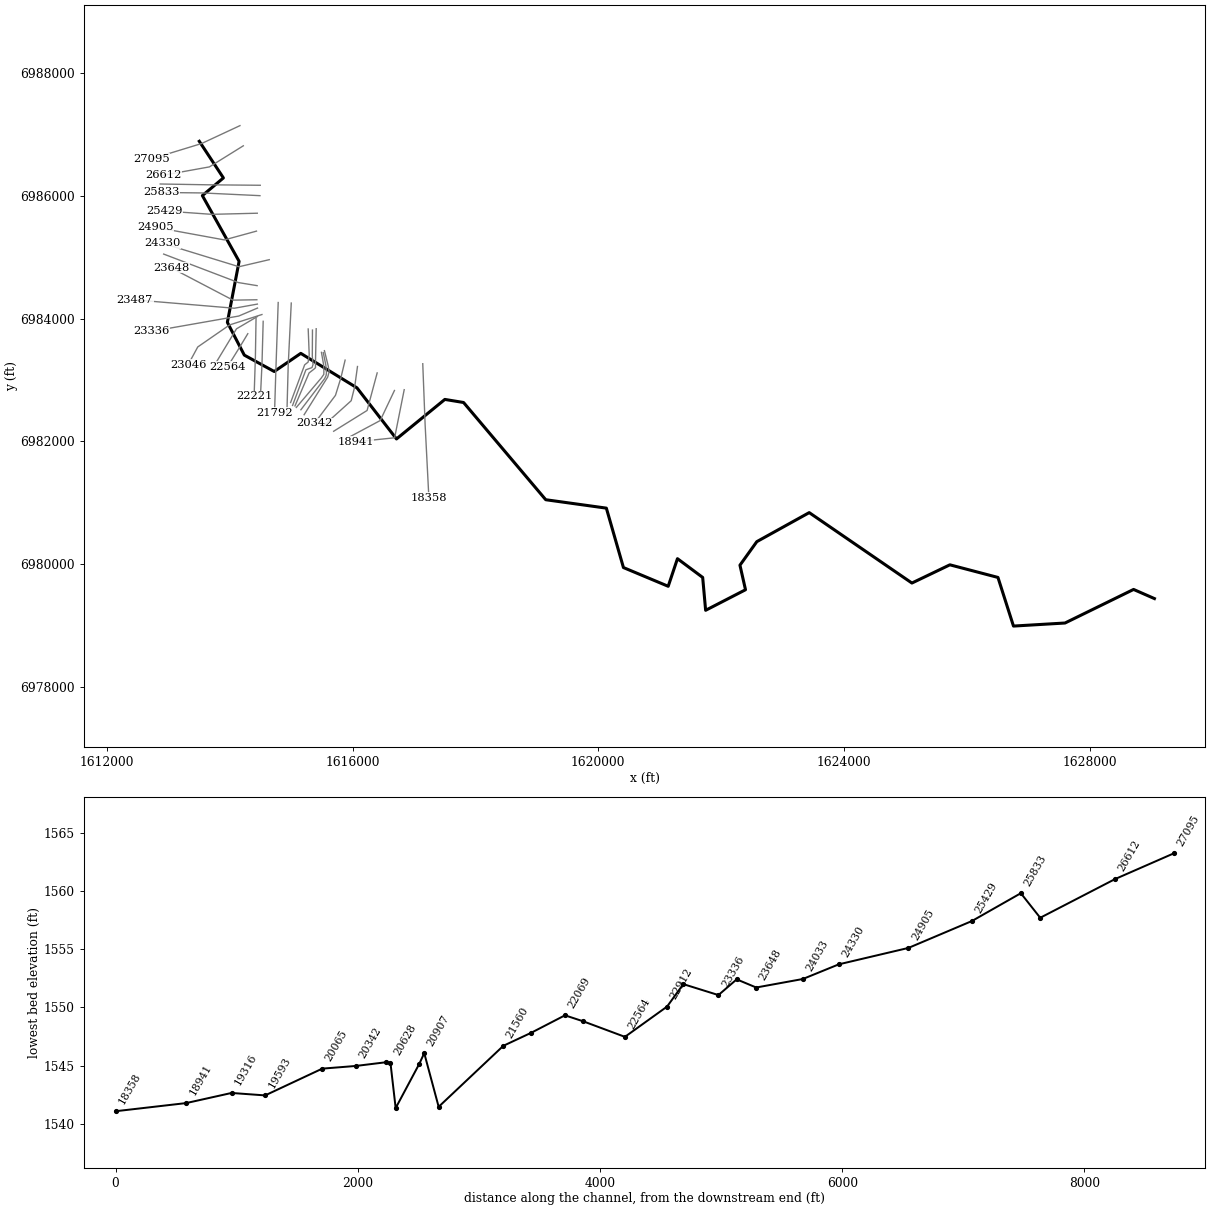
--- Post Oak Creek.prj (project) ---

Proj Title=Post Oak Creek Base Level Engineering
Current Plan=p01
Default Exp/Contr=0.3,0.1
English Units
Geom File=g01
Flow File=f01
Plan File=p01
Y Axis Title=Elevation
X Axis Title(PF)=Main Channel Distance
X Axis Title(XS)=Station
BEGIN DESCRIPTION:
Post Oak Creek
END DESCRIPTION:
DSS Export Rating Curves= 0
DSS Export Rating Curve Sorted= 0
DSS Export Volume Flow Curves= 0
DXF OffsetX= 0
DXF OffsetY= 0
DXF ScaleX= 1
DXF ScaleY= 10

--- Post Oak Creek.p01 (plan) ---

Plan Title=Multiple Run
Short Identifier=Multiple
Geom File=g01
Flow File=f01
Subcritical Flow
K Sum by GR= 0
Std Step Tol= 0.01
Critical Tol= 0.01
Num of Std Step Trials= 20
Max Error Tol= 0.3
Flow Tol Ratio= 0.001
Split Flow NTrial= 30
Split Flow Tol= 0.02
Split Flow Ratio= 0.02
Log Output Level= 0
Friction Slope Method= 1
Unsteady Friction Slope Method= 2
Unsteady Bridges Friction Slope Method= 1
Parabolic Critical Depth
Global Vel Dist=  1 , 1 , 1
Global Log Level= 0
CheckData=True
Encroach Param= -1, 0, 0, 0
BEGIN DESCRIPTION:
Multiple Run
END DESCRIPTION:

--- Post Oak Creek.f01 (steady flow) ---

Flow Title=Multiple
Number of Profiles=7
Profile Names=10-year,25-year,50-year,1pct_min,100-year,1pct_plu,500-year
River Rch & RM= Post Oak Creek,Reach-1,27095
     176     236     283     169     337     673     485
River Rch & RM= Post Oak Creek,Reach-1,25833
     232     314     380     229     457     913     670
River Rch & RM= Post Oak Creek,Reach-1,22912
     419     589     731     451     899    1794    1378
River Rch & RM= Post Oak Creek,Reach-1,18358
     651     931    1170     729    1454    2901    2278
River Rch & RM= Post Oak Creek,Reach-1,14561
     643     915    1145     710    1416    2826    2199
River Rch & RM= Post Oak Creek,Reach-1,10002
     675     961    1203     746    1489    2971    2313
River Rch & RM= Post Oak Creek,Reach-1,6963
     819    1172    1471     915    1826    3643    2850
Boundary for River Rch & Prof#=Post Oak Creek,Reach-1,1
Up Type=0
Dn Type=3
Dn Slope=0.005
Boundary for River Rch & Prof#=Post Oak Creek,Reach-1,2
Up Type=0
Dn Type=3
Dn Slope=0.005
Boundary for River Rch & Prof#=Post Oak Creek,Reach-1,3
Up Type=0
Dn Type=3
Dn Slope=0.005
Boundary for River Rch & Prof#=Post Oak Creek,Reach-1,4
Up Type=0
Dn Type=3
Dn Slope=0.005
Boundary for River Rch & Prof#=Post Oak Creek,Reach-1,5
Up Type=0
Dn Type=3
Dn Slope=0.005
Boundary for River Rch & Prof#=Post Oak Creek,Reach-1,6
Up Type=0
Dn Type=3
Dn Slope=0.005
Boundary for River Rch & Prof#=Post Oak Creek,Reach-1,7
Up Type=0
Dn Type=3
Dn Slope=0.005

--- Post Oak Creek.g01 (geometry) ---

Geom Title=Existing Conditions

River Reach=Post Oak Creek,Reach-1
Reach XY= 30
      1613505.00      6986888.00      1613897.50      6986291.13
      1613554.95      6986003.34      1614153.03      6984932.35
      1613961.88      6983938.03      1614237.86      6983404.28
      1614725.04      6983137.39      1615157.28      6983432.95
      1616071.67      6982871.35      1616715.34      6982038.81
      1617502.55      6982682.55      1617807.43      6982632.48
      1619145.20      6981048.48      1620132.01      6980911.52
      1620410.18      6979943.44      1621138.98      6979638.24
      1621289.70      6980088.17      1621700.24      6979782.42
      1621748.33      6979246.95      1622397.54      6979581.95
      1622307.06      6979982.15      1622581.59      6980365.57
      1623434.79      6980838.52      1625106.64      6979691.14
      1625724.88      6979988.09      1626507.43      6979782.48
      1626760.24      6978990.09      1627599.12      6979039.96
      1628715.55      6979586.92      1629055.00      6979438.00

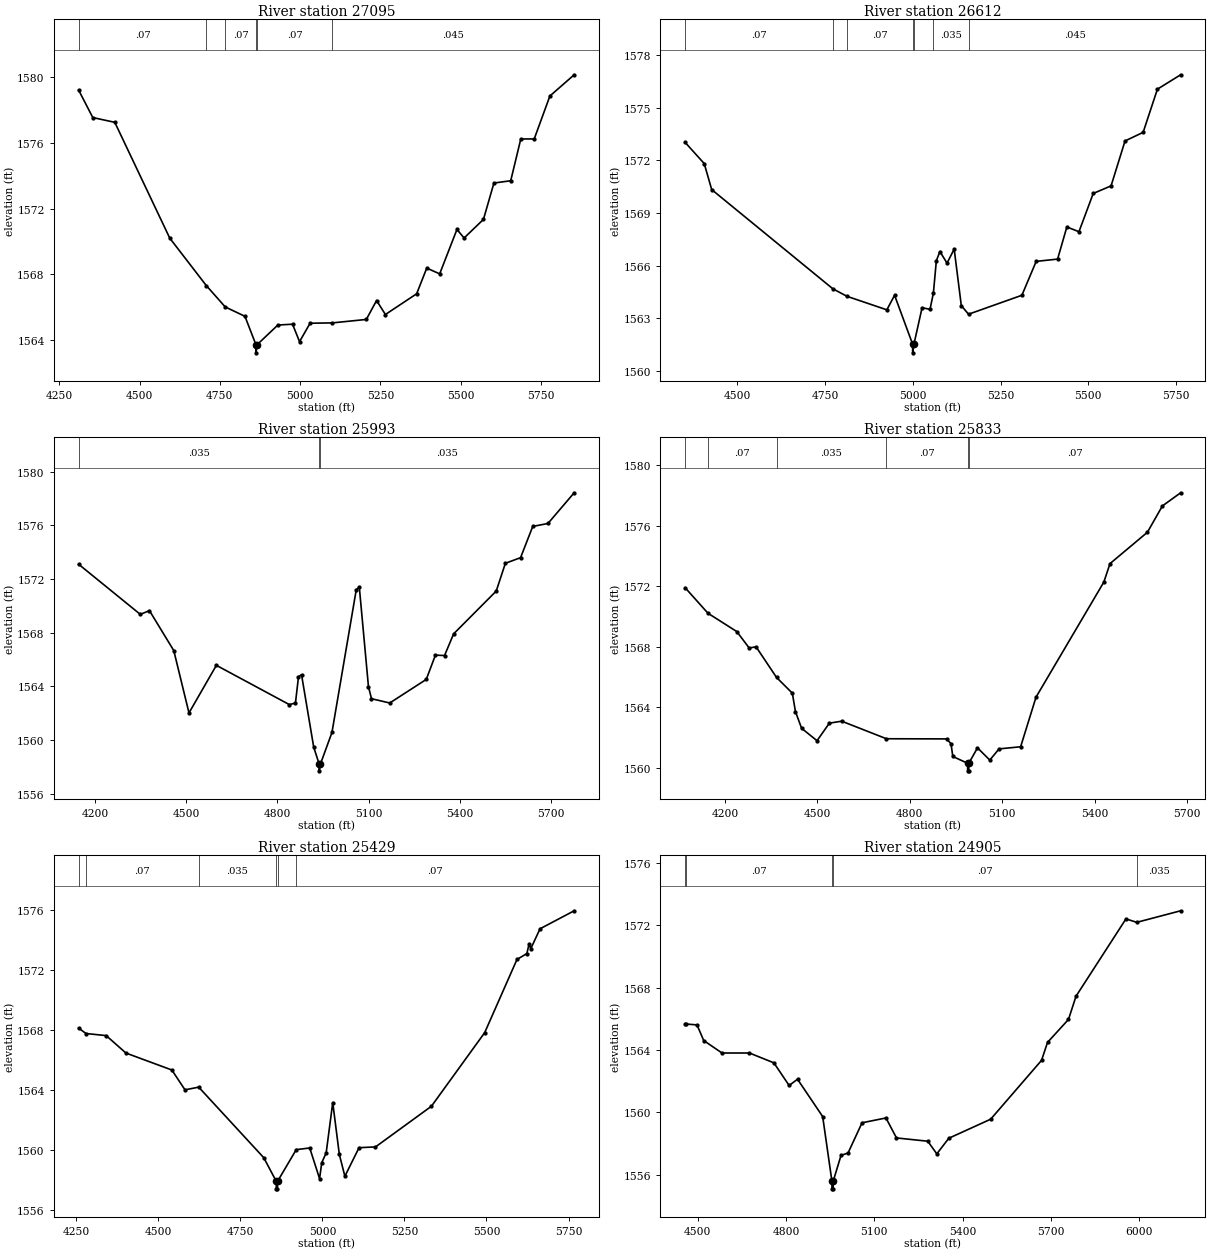
Type RM Length L Ch R = 1,27095,483,483,483
BEGIN DESCRIPTION:
Post Oak Creek 44.0
END DESCRIPTION:
XS GIS Cut Line= 3
      1614167.03      6987143.04      1613542.01      6986851.44
      1612726.07      6986601.38
#Sta/Elev= 30
  4310.3 1579.20  4354.4 1577.53  4422.9 1577.24  4594.1 1570.20  4707.8 1567.32
  4766.8 1566.02  4828.2 1565.45  4862.3 1563.73  4862.5 1563.23  4866.3 1563.73
  4930.7 1564.92  4976.4 1564.97  4998.2 1563.91  5031.1 1565.03  5100.4 1565.05
  5206.1 1565.26  5238.1 1566.41  5265.6 1565.56  5362.9 1566.82  5394.3 1568.38
  5434.6 1568.03  5488.4 1570.73  5510.6 1570.21  5570.9 1571.34  5603.5 1573.55
  5655.8 1573.69  5687.2 1576.23  5729.0 1576.23  5777.8 1578.84  5853.4 1580.13
#Mann=6,-1,0
  4310.3    0.07       0  4707.8   0.035       0  4766.8    0.07       0
  4862.3    0.07       0  4866.3    0.07       0  5100.4   0.045       0
Bank Sta=4862.3,4866.3
Exp/Cntr=0.3,0.1

Type RM Length L Ch R = 1,26612,619,619,619
BEGIN DESCRIPTION:
Mapping XS a5cedaad
END DESCRIPTION:
XS GIS Cut Line= 3
      1614221.75      6986814.71      1613669.68      6986470.96
      1612919.84      6986335.58
#Sta/Elev= 30
  4350.7 1573.02  4405.3 1571.81  4426.5 1570.33  4771.7 1564.68  4812.1 1564.25
  4925.7 1563.48  4947.7 1564.31  4999.0 1561.53  4999.3 1561.03  5003.0 1561.53
  5026.1 1563.60  5048.7 1563.51  5058.3 1564.43  5066.8 1566.28  5076.9 1566.80
  5097.2 1566.14  5117.6 1566.94  5137.9 1563.72  5158.5 1563.23  5310.6 1564.31
  5351.3 1566.24  5412.3 1566.37  5438.7 1568.20  5473.2 1567.93  5513.9 1570.11
  5564.7 1570.54  5604.5 1573.10  5656.1 1573.59  5696.8 1576.05  5763.0 1576.87
#Mann=7,-1,0
  4350.7    0.07       0  4771.7   0.035       0  4812.1    0.07       0
  4999.0    0.07       0  5003.0    0.07       0  5058.3   0.035       0
  5158.5   0.045       0
Bank Sta=4999,5003
Exp/Cntr=0.3,0.1

Type RM Length L Ch R = 1,25993,160,160,160
BEGIN DESCRIPTION:
Mapping XS b6853bab
END DESCRIPTION:
XS GIS Cut Line= 3
      1614497.79      6986171.49      1613638.43      6986179.30
      1612868.83      6986192.30
#Sta/Elev= 30
  4146.3 1573.11  4349.1 1569.37  4379.1 1569.65  4459.1 1566.67  4509.1 1562.02
  4599.1 1565.57  4839.1 1562.64  4859.1 1562.76  4869.1 1564.72  4879.1 1564.87
  4919.1 1559.47  4937.1 1558.20  4937.4 1557.70  4941.1 1558.20  4979.1 1560.56
  5059.1 1571.22  5069.1 1571.39  5099.1 1563.98  5109.1 1563.08  5169.1 1562.76
  5289.2 1564.52  5319.2 1566.33  5349.2 1566.30  5379.2 1567.92  5519.2 1571.11
  5549.2 1573.18  5599.2 1573.60  5639.2 1575.93  5689.2 1576.15  5775.4 1578.44
#Mann=3,-1,0
  4146.3   0.035       0  4937.1   0.035       0  4941.1   0.035       0
Bank Sta=4937.1,4941.1
Exp/Cntr=0.3,0.1

Type RM Length L Ch R = 1,25833,404,404,404
BEGIN DESCRIPTION:
Mapping XS c672449b
END DESCRIPTION:
XS GIS Cut Line= 3
      1614492.60      6986002.21      1613557.70      6986046.49
      1612885.80      6986054.30
#Sta/Elev= 30
  4070.8 1571.91  4145.1 1570.22  4238.6 1569.01  4278.6 1567.93  4301.2 1568.00
  4367.5 1565.98  4418.8 1564.94  4428.8 1563.73  4448.8 1562.62  4498.9 1561.80
  4538.9 1562.96  4579.0 1563.09  4724.1 1561.93  4919.4 1561.92  4933.7 1561.60
  4939.4 1560.76  4987.4 1560.31  4987.7 1559.81  4991.2 1559.81  4991.4 1560.31
  5019.5 1561.33  5059.5 1560.52  5089.5 1561.26  5159.5 1561.40  5209.5 1564.68
  5429.5 1572.28  5449.5 1573.50  5570.8 1575.57  5619.5 1577.31  5678.7 1578.18
#Mann=6,-1,0
  4070.8   0.035       0  4145.1    0.07       0  4367.5   0.035       0
  4724.1    0.07       0  4987.4    0.07       0  4991.4    0.07       0
Bank Sta=4987.4,4991.4
Exp/Cntr=0.3,0.1

Type RM Length L Ch R = 1,25429,524,524,524
BEGIN DESCRIPTION:
Mapping XS acf539b9
END DESCRIPTION:
XS GIS Cut Line= 3
      1614449.01      6985716.19      1613706.83      6985697.96
      1612941.19      6985752.65
#Sta/Elev= 30
  4257.2 1568.12  4279.7 1567.76  4341.2 1567.62  4401.3 1566.46  4541.3 1565.33
  4581.3 1564.01  4623.1 1564.19  4821.4 1559.49  4859.4 1557.92  4859.6 1557.42
  4863.1 1557.42  4863.4 1557.92  4920.3 1560.03  4961.4 1560.14  4991.4 1558.10
  4998.0 1559.16  5011.5 1559.81  5031.5 1563.16  5051.6 1559.71  5068.5 1558.26
  5111.7 1560.16  5161.8 1560.21  5332.3 1562.92  5494.6 1567.82  5592.9 1572.69
  5623.0 1573.08  5629.9 1573.73  5634.9 1573.40  5663.1 1574.73  5767.2 1575.93
#Mann=6,-1,0
  4257.2   0.035       0  4279.7    0.07       0  4623.1   0.035       0
  4859.4    0.07       0  4863.4   0.035       0  4920.3    0.07       0
Bank Sta=4859.4,4863.4
Exp/Cntr=0.3,0.1

Type RM Length L Ch R = 1,24905,575,575,575
BEGIN DESCRIPTION:
Mapping XS 368c1f5a
END DESCRIPTION:
XS GIS Cut Line= 3
      1614435.97      6985424.52      1613912.56      6985281.29
      1612790.11      6985487.03
#Sta/Elev= 30
  4456.9 1565.67  4458.3 1565.67  4497.4 1565.61  4520.1 1564.61  4582.3 1563.81
  4675.6 1563.81  4758.6 1563.18  4810.4 1561.73  4838.9 1562.13  4924.4 1559.74
  4955.7 1555.61  4956.0 1555.11  4960.0 1555.11  4960.3 1555.61  4986.7 1557.25
  5010.7 1557.41  5058.1 1559.34  5139.4 1559.65  5175.2 1558.37  5281.5 1558.16
  5312.2 1557.35  5352.9 1558.35  5495.2 1559.57  5668.1 1563.34  5688.4 1564.49
  5759.6 1565.96  5785.3 1567.45  5954.9 1572.40  5991.7 1572.18  6140.7 1572.92
#Mann=5,-1,0
  4456.9   0.035       0  4458.3    0.07       0  4955.7    0.07       0
  4960.3    0.07       0  5991.7   0.035       0
Bank Sta=4955.7,4960.3
Exp/Cntr=0.3,0.1

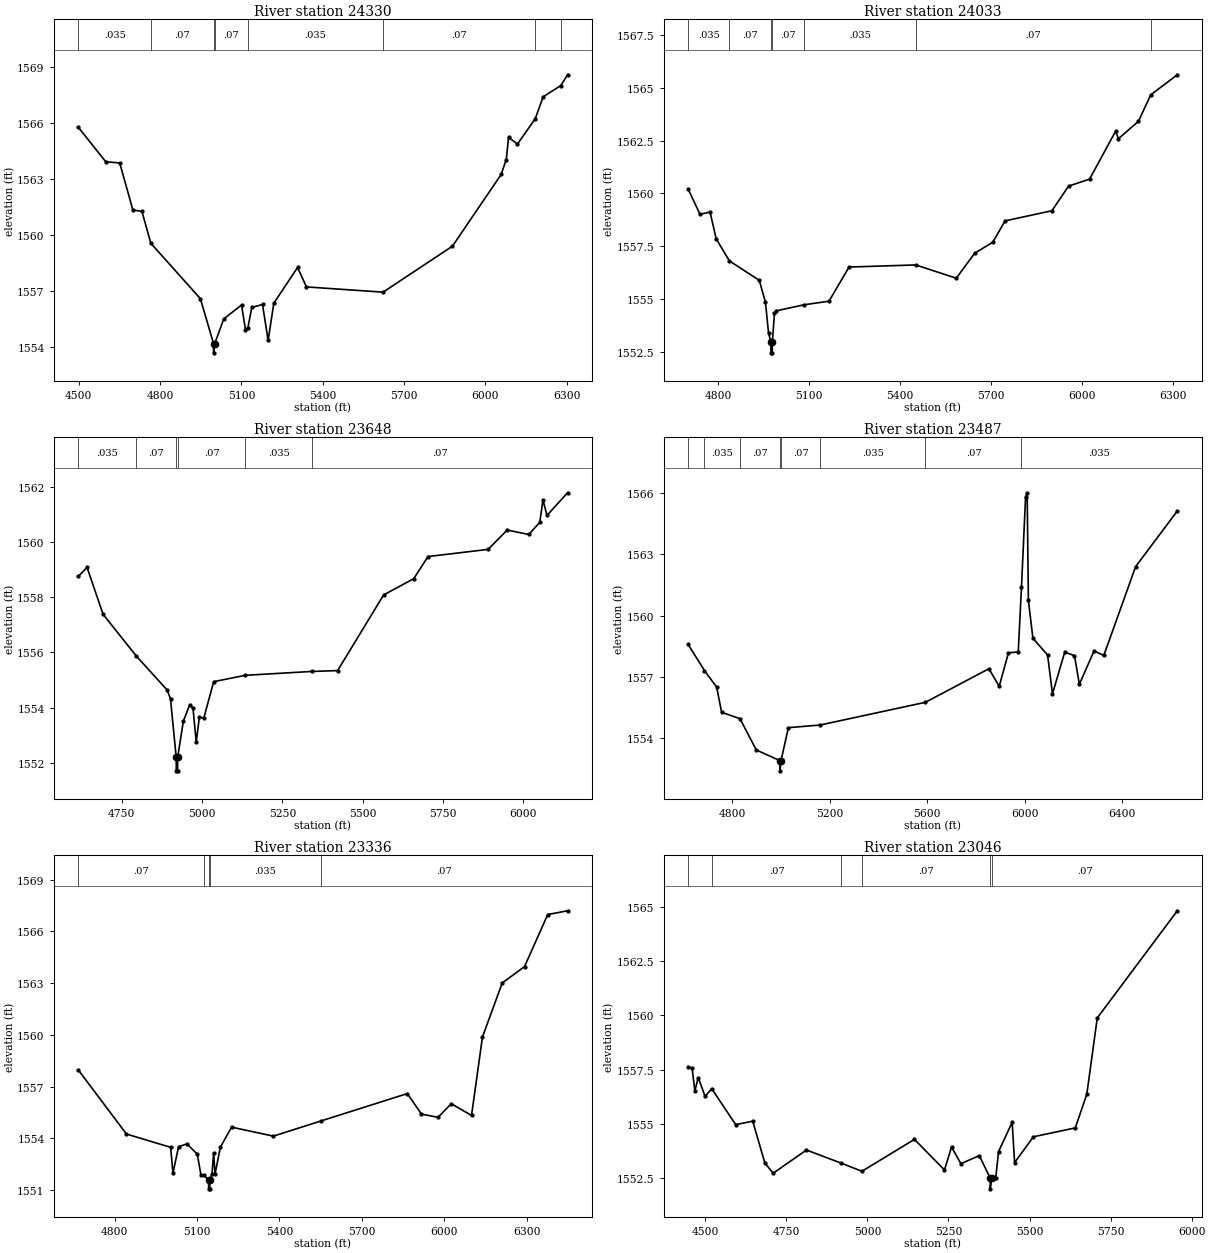
Type RM Length L Ch R = 1,24330,297,297,297
BEGIN DESCRIPTION:
Mapping XS 6cd703d5
END DESCRIPTION:
XS GIS Cut Line= 3
      1614643.74      6984959.34      1614151.16      6984844.34
      1612908.87      6985225.91
#Sta/Elev= 30
  4498.2 1565.78  4599.6 1563.93  4650.9 1563.87  4699.6 1561.35  4733.1 1561.27
  4765.7 1559.57  4948.7 1556.60  4997.1 1554.20  4997.5 1553.70  5001.8 1554.20
  5035.1 1555.52  5100.5 1556.26  5115.1 1554.94  5124.0 1555.05  5138.5 1556.13
  5177.9 1556.29  5198.7 1554.37  5219.7 1556.36  5307.3 1558.27  5340.0 1557.23
  5622.9 1556.95  5878.7 1559.41  6058.5 1563.25  6077.5 1564.05  6086.0 1565.24
  6118.8 1564.88  6184.6 1566.24  6213.5 1567.41  6278.6 1568.01  6303.6 1568.59
#Mann=8,-1,0
  4498.2   0.035       0  4765.7    0.07       0  4997.1    0.07       0
  5001.8    0.07       0  5124.0   0.035       0  5622.9    0.07       0
  6184.6   0.035       0  6278.6    0.07       0
Bank Sta=4997.1,5001.8
Exp/Cntr=0.3,0.1

Type RM Length L Ch R = 1,24033,385,385,385
BEGIN DESCRIPTION:
Mapping XS f3305473
END DESCRIPTION:
XS GIS Cut Line= 3
      1614446.32      6984536.18      1614142.48      6984586.09
      1612925.06      6985050.49
#Sta/Elev= 30
  4701.9 1560.21  4741.3 1559.01  4774.2 1559.12  4794.4 1557.85  4838.0 1556.80
  4936.3 1555.88  4956.6 1554.84  4966.7 1553.40  4974.5 1552.94  4974.8 1552.44
  4978.9 1552.44  4979.3 1552.94  4986.3 1554.31  4991.4 1554.43  5084.0 1554.72
  5165.9 1554.89  5231.9 1556.51  5451.4 1556.61  5585.0 1555.98  5645.2 1557.16
  5705.4 1557.69  5745.6 1558.70  5899.9 1559.18  5954.7 1560.35  6023.9 1560.68
  6109.5 1562.95  6119.1 1562.60  6184.7 1563.42  6225.3 1564.68  6312.8 1565.63
#Mann=7,-1,0
  4701.9   0.035       0  4838.0    0.07       0  4974.5    0.07       0
  4979.3    0.07       0  5084.0   0.035       0  5451.4    0.07       0
  6225.3   0.035       0
Bank Sta=4974.5,4979.3
Exp/Cntr=0.3,0.1

Type RM Length L Ch R = 1,23648,161,161,161
BEGIN DESCRIPTION:
Mapping XS 5f2d4215
END DESCRIPTION:
XS GIS Cut Line= 3
      1614442.06      6984306.43      1614053.65      6984299.92
      1613048.33      6984826.41
#Sta/Elev= 30
  4614.5 1558.75  4641.6 1559.08  4691.6 1557.38  4794.9 1555.87  4891.6 1554.63
  4901.6 1554.31  4919.2 1552.21  4919.6 1551.71  4923.7 1551.71  4924.0 1552.21
  4941.6 1553.51  4961.6 1554.11  4971.6 1553.98  4981.6 1552.75  4991.6 1553.67
  5005.0 1553.61  5036.0 1554.94  5135.0 1555.17  5341.6 1555.31  5421.9 1555.34
  5565.1 1558.08  5659.0 1558.67  5703.2 1559.47  5890.5 1559.73  5949.7 1560.43
  6017.2 1560.27  6051.3 1560.71  6061.3 1561.52  6073.8 1560.96  6137.8 1561.78
#Mann=6,-1,0
  4614.5   0.035       0  4794.9    0.07       0  4919.2    0.07       0
  4924.0    0.07       0  5135.0   0.035       0  5341.6    0.07       0
Bank Sta=4919.2,4924
Exp/Cntr=0.3,0.1

Type RM Length L Ch R = 1,23487,151,151,151
BEGIN DESCRIPTION:
Mapping XS 7e564298
END DESCRIPTION:
XS GIS Cut Line= 3
      1614450.44      6984235.67      1614074.76      6984168.16
      1612454.50      6984304.59
#Sta/Elev= 30
  4618.3 1558.59  4685.6 1557.31  4735.6 1556.50  4755.9 1555.27  4831.3 1554.96
  4898.2 1553.43  4994.9 1552.91  4995.3 1552.41  4999.7 1552.91  5029.9 1554.52
  5160.4 1554.65  5592.3 1555.76  5852.8 1557.40  5895.0 1556.54  5933.1 1558.18
  5973.2 1558.22  5986.5 1561.39  6003.3 1565.80  6009.8 1566.00  6014.8 1560.74
  6033.4 1558.89  6093.6 1558.07  6113.7 1556.17  6163.9 1558.21  6204.0 1558.04
  6224.1 1556.64  6284.3 1558.27  6324.4 1558.05  6454.9 1562.39  6626.0 1565.11
#Mann=8,-1,0
  4618.3    0.07       0  4685.6   0.035       0  4831.3    0.07       0
  4994.9    0.07       0  4999.7    0.07       0  5160.4   0.035       0
  5592.3    0.07       0  5986.5   0.035       0
Bank Sta=4994.9,4999.7
Exp/Cntr=0.3,0.1

Type RM Length L Ch R = 1,23336,290,290,290
BEGIN DESCRIPTION:
Mapping XS b4b50856
END DESCRIPTION:
XS GIS Cut Line= 3
      1614452.64      6984170.99      1614146.67      6984040.79
      1612720.86      6983790.14
#Sta/Elev= 30
  4668.1 1557.96  4843.3 1554.24  5004.0 1553.47  5012.5 1551.97  5032.8 1553.50
  5063.2 1553.67  5101.1 1553.07  5114.0 1551.89  5125.9 1551.85  5142.0 1551.56
  5142.4 1551.06  5146.5 1551.06  5146.9 1551.56  5154.6 1551.92  5160.4 1553.15
  5165.5 1551.91  5185.1 1553.48  5225.7 1554.64  5378.0 1554.12  5551.1 1555.00
  5865.4 1556.59  5916.6 1555.40  5977.0 1555.21  6025.1 1556.00  6098.9 1555.32
  6138.7 1559.87  6210.6 1563.01  6291.8 1563.96  6376.1 1566.98  6448.3 1567.20
#Mann=5,-1,0
  4668.1    0.07       0  5125.9   0.035       0  5142.0    0.07       0
  5146.9   0.035       0  5551.1    0.07       0
Bank Sta=5142,5146.9
Exp/Cntr=0.3,0.1

Type RM Length L Ch R = 1,23046,134,134,134
BEGIN DESCRIPTION:
Mapping XS 3244a0ff
END DESCRIPTION:
XS GIS Cut Line= 4
      1614524.86      6984065.73      1613998.28      6983896.18
      1613479.96      6983537.49      1613324.86      6983251.35
#Sta/Elev= 30
  4446.8 1557.63  4459.1 1557.56  4467.7 1556.52  4478.2 1557.13  4499.2 1556.26
  4519.6 1556.62  4593.7 1554.96  4646.2 1555.12  4683.6 1553.19  4709.3 1552.72
  4811.9 1553.79  4919.8 1553.18  4983.0 1552.81  5145.0 1554.28  5237.6 1552.87
  5259.4 1553.93  5288.3 1553.16  5345.0 1553.53  5378.5 1552.50  5378.9 1552.00
  5383.4 1552.50  5395.7 1552.51  5404.5 1553.72  5446.4 1555.07  5453.9 1553.21
  5511.9 1554.40  5641.1 1554.81  5676.6 1556.36  5708.9 1559.88  5955.8 1564.82
#Mann=6,-1,0
  4446.8   0.035       0  4519.6    0.07       0  4919.8   0.035       0
  4983.0    0.07       0  5378.5    0.07       0  5383.4    0.07       0
Bank Sta=5378.5,5383.4
Exp/Cntr=0.3,0.1

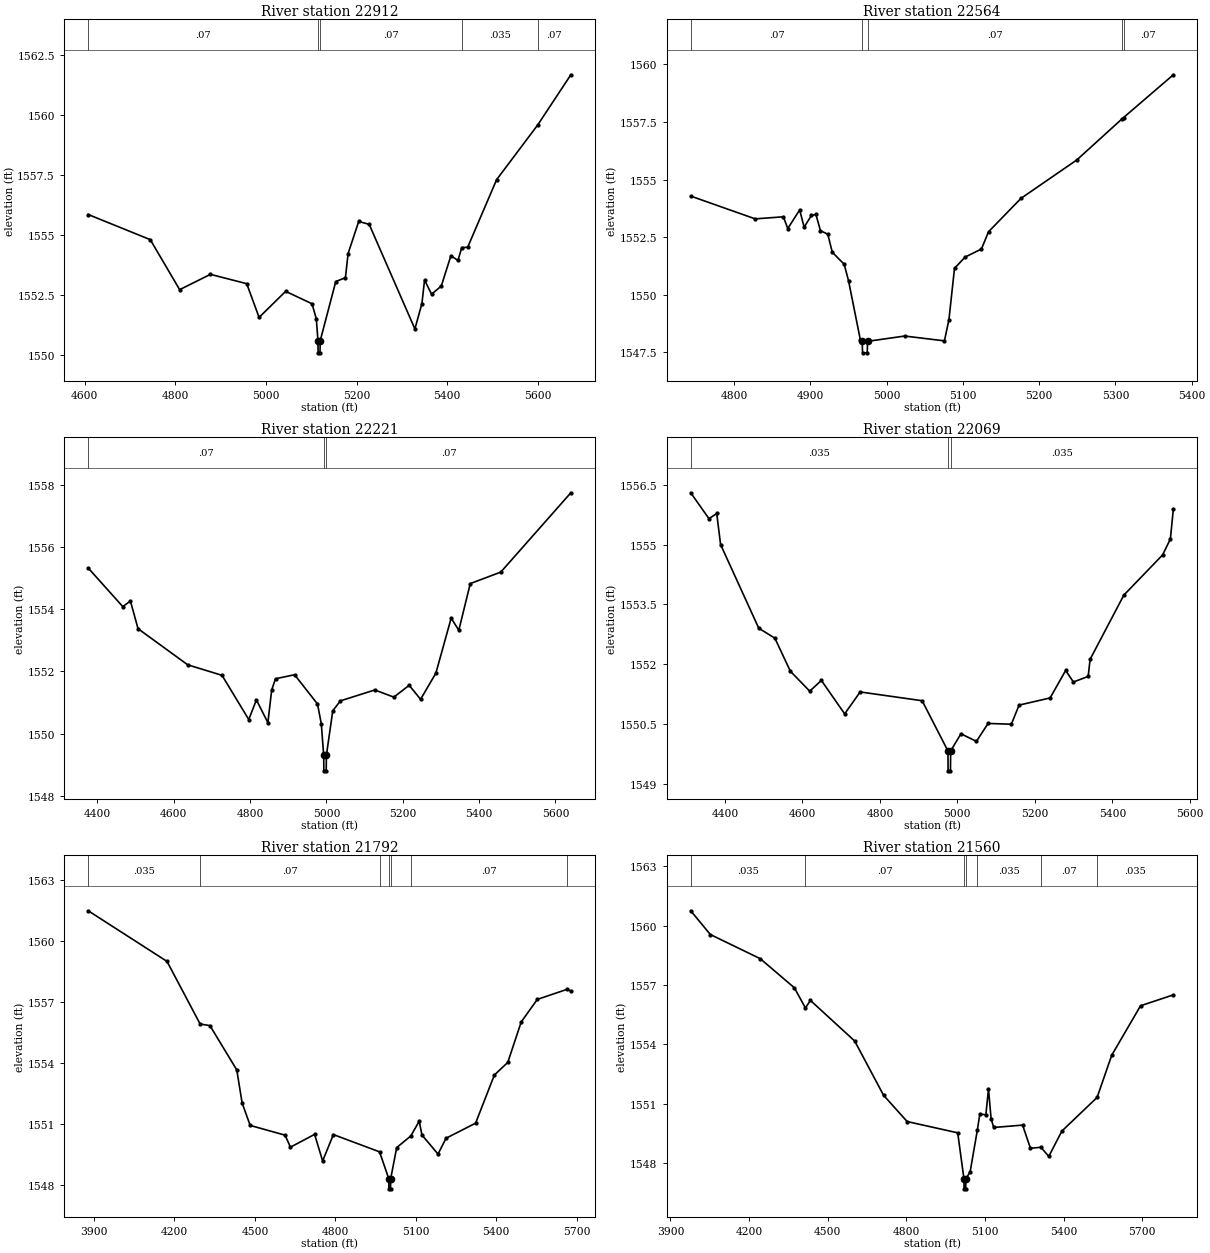
Type RM Length L Ch R = 1,22912,348,348,348
BEGIN DESCRIPTION:
Mapping XS 27460a36
END DESCRIPTION:
XS GIS Cut Line= 3
      1614448.76      6984032.04      1614110.48      6983832.68
      1613762.48      6983257.51
#Sta/Elev= 30
  4607.8 1555.85  4744.7 1554.80  4809.5 1552.71  4877.5 1553.35  4957.5 1552.96
  4984.8 1551.55  5043.4 1552.64  5101.6 1552.12  5111.1 1551.49  5114.7 1550.57
  5115.0 1550.07  5119.2 1550.07  5119.6 1550.57  5154.0 1553.05  5175.3 1553.21
  5181.2 1554.22  5204.6 1555.56  5227.7 1555.44  5328.6 1551.07  5344.1 1552.13
  5349.9 1553.11  5365.4 1552.52  5386.8 1552.86  5408.1 1554.13  5423.6 1553.93
  5432.0 1554.47  5445.0 1554.48  5509.0 1557.31  5599.5 1559.59  5672.7 1561.69
#Mann=5,-1,0
  4607.8    0.07       0  5114.7    0.07       0  5119.6    0.07       0
  5432.0   0.035       0  5599.5    0.07       0
Bank Sta=5114.7,5119.6
Exp/Cntr=0.3,0.1

Type RM Length L Ch R = 1,22564,343,343,343
BEGIN DESCRIPTION:
Mapping XS e2e03882
END DESCRIPTION:
XS GIS Cut Line= 3
      1614294.64      6983753.57      1614163.11      6983534.79
      1613963.89      6983214.47
#Sta/Elev= 30
  4743.4 1554.28  4827.9 1553.29  4864.8 1553.38  4870.6 1552.87  4886.2 1553.68
  4892.0 1552.93  4901.6 1553.44  4907.5 1553.48  4913.4 1552.78  4923.1 1552.62
  4928.9 1551.84  4944.5 1551.32  4950.3 1550.59  4965.8 1548.02  4968.1 1547.97
  4968.6 1547.47  4974.7 1547.47  4975.2 1547.97  5023.9 1548.20  5075.9 1547.99
  5081.8 1548.91  5089.1 1551.14  5103.0 1551.63  5124.4 1551.98  5133.7 1552.73
  5176.2 1554.18  5249.4 1555.85  5309.2 1557.65  5310.6 1557.69  5375.9 1559.55
#Mann=5,-1,0
  4743.4    0.07       0  4968.1    0.07       0  4975.2    0.07       0
  5309.2   0.035       0  5310.6    0.07       0
Bank Sta=4968.1,4975.2
Exp/Cntr=0.3,0.1

Type RM Length L Ch R = 1,22221,152,152,152
BEGIN DESCRIPTION:
Mapping XS e427e591
END DESCRIPTION:
XS GIS Cut Line= 3
      1614428.65      6983998.49      1614418.24      6983373.50
      1614397.40      6982734.62
#Sta/Elev= 30
  4376.1 1555.32  4466.6 1554.08  4486.6 1554.26  4506.6 1553.37  4636.6 1552.21
  4726.6 1551.87  4796.6 1550.45  4816.7 1551.08  4846.7 1550.35  4856.7 1551.40
  4866.7 1551.76  4916.7 1551.89  4976.7 1550.95  4986.7 1550.31  4992.9 1549.30
  4993.4 1548.80  4999.5 1548.80  5000.0 1549.30  5016.7 1550.73  5036.7 1551.05
  5126.7 1551.40  5176.8 1551.17  5216.8 1551.55  5246.8 1551.10  5286.8 1551.94
  5326.9 1553.71  5346.9 1553.32  5376.9 1554.82  5456.9 1555.19  5640.4 1557.74
#Mann=3,-1,0
  4376.1    0.07       0  4992.9    0.07       0  5000.0    0.07       0
Bank Sta=4992.9,5000
Exp/Cntr=0.3,0.1

Type RM Length L Ch R = 1,22069,277,277,277
BEGIN DESCRIPTION:
Mapping XS 200cd539
END DESCRIPTION:
XS GIS Cut Line= 3
      1614544.97      6983955.10      1614525.87      6983267.60
      1614499.92      6982710.37
#Sta/Elev= 30
  4311.8 1556.30  4358.9 1555.65  4378.9 1555.78  4388.9 1555.00  4487.4 1552.90
  4529.0 1552.65  4569.0 1551.82  4619.0 1551.32  4649.0 1551.59  4709.1 1550.75
  4749.1 1551.30  4909.1 1551.08  4975.6 1549.82  4976.1 1549.32  4982.2 1549.32
  4982.7 1549.82  5009.2 1550.25  5049.2 1550.06  5079.3 1550.51  5139.3 1550.49
  5159.3 1550.97  5239.4 1551.15  5279.5 1551.84  5299.5 1551.55  5337.6 1551.69
  5342.6 1552.12  5429.6 1553.73  5529.7 1554.74  5549.8 1555.14  5557.4 1555.89
#Mann=3,-1,0
  4311.8   0.035       0  4975.6   0.035       0  4982.7   0.035       0
Bank Sta=4975.6,4982.7
Exp/Cntr=0.3,0.1

Type RM Length L Ch R = 1,21792,232,232,232
BEGIN DESCRIPTION:
Mapping XS 553d01d6
END DESCRIPTION:
XS GIS Cut Line= 3
      1614789.53      6984261.56      1614751.02      6983143.96
      1614730.00      6982462.95
#Sta/Elev= 30
  3878.6 1561.51  4172.3 1559.02  4295.8 1555.94  4332.4 1555.86  4432.5 1553.68
  4452.5 1552.05  4482.5 1550.95  4612.6 1550.47  4632.6 1549.88  4722.7 1550.51
  4752.7 1549.20  4792.7 1550.50  4964.9 1549.65  4999.2 1548.33  4999.7 1547.83
  5005.9 1547.83  5006.4 1548.33  5028.9 1549.86  5081.3 1550.43  5112.9 1551.16
  5122.9 1550.48  5182.9 1549.54  5212.9 1550.32  5323.0 1551.06  5393.0 1553.43
  5443.0 1554.05  5493.1 1556.04  5553.1 1557.15  5663.0 1557.64  5678.2 1557.57
#Mann=7,-1,0
  3878.6   0.035       0  4295.8    0.07       0  4964.9   0.035       0
  4999.2   0.035       0  5006.4   0.035       0  5081.3    0.07       0
  5663.0   0.035       0
Bank Sta=4999.2,5006.4
Exp/Cntr=0.3,0.1

Type RM Length L Ch R = 1,21560,534,534,534
BEGIN DESCRIPTION:
Mapping XS 908c9a8f
END DESCRIPTION:
XS GIS Cut Line= 3
      1615002.20      6984252.84      1614952.41      6983237.71
      1614930.00      6982412.97
#Sta/Elev= 30
  3977.4 1560.75  4052.3 1559.55  4242.6 1558.33  4372.7 1556.86  4415.0 1555.84
  4434.2 1556.22  4603.0 1554.17  4713.1 1551.43  4803.2 1550.10  4996.1 1549.53
  5019.9 1547.20  5020.4 1546.70  5026.6 1546.70  5027.1 1547.20  5043.5 1547.56
  5070.8 1549.65  5080.5 1550.48  5103.5 1550.44  5113.5 1551.74  5123.5 1550.24
  5133.5 1549.80  5243.6 1549.92  5273.6 1548.75  5313.3 1548.80  5343.6 1548.34
  5393.6 1549.62  5528.0 1551.32  5583.7 1553.45  5693.7 1555.95  5818.8 1556.50
#Mann=7,-1,0
  3977.4   0.035       0  4415.0    0.07       0  5019.9    0.07       0
  5027.1    0.07       0  5070.8   0.035       0  5313.3    0.07       0
  5528.0   0.035       0
Bank Sta=5019.9,5027.1
Exp/Cntr=0.3,0.1

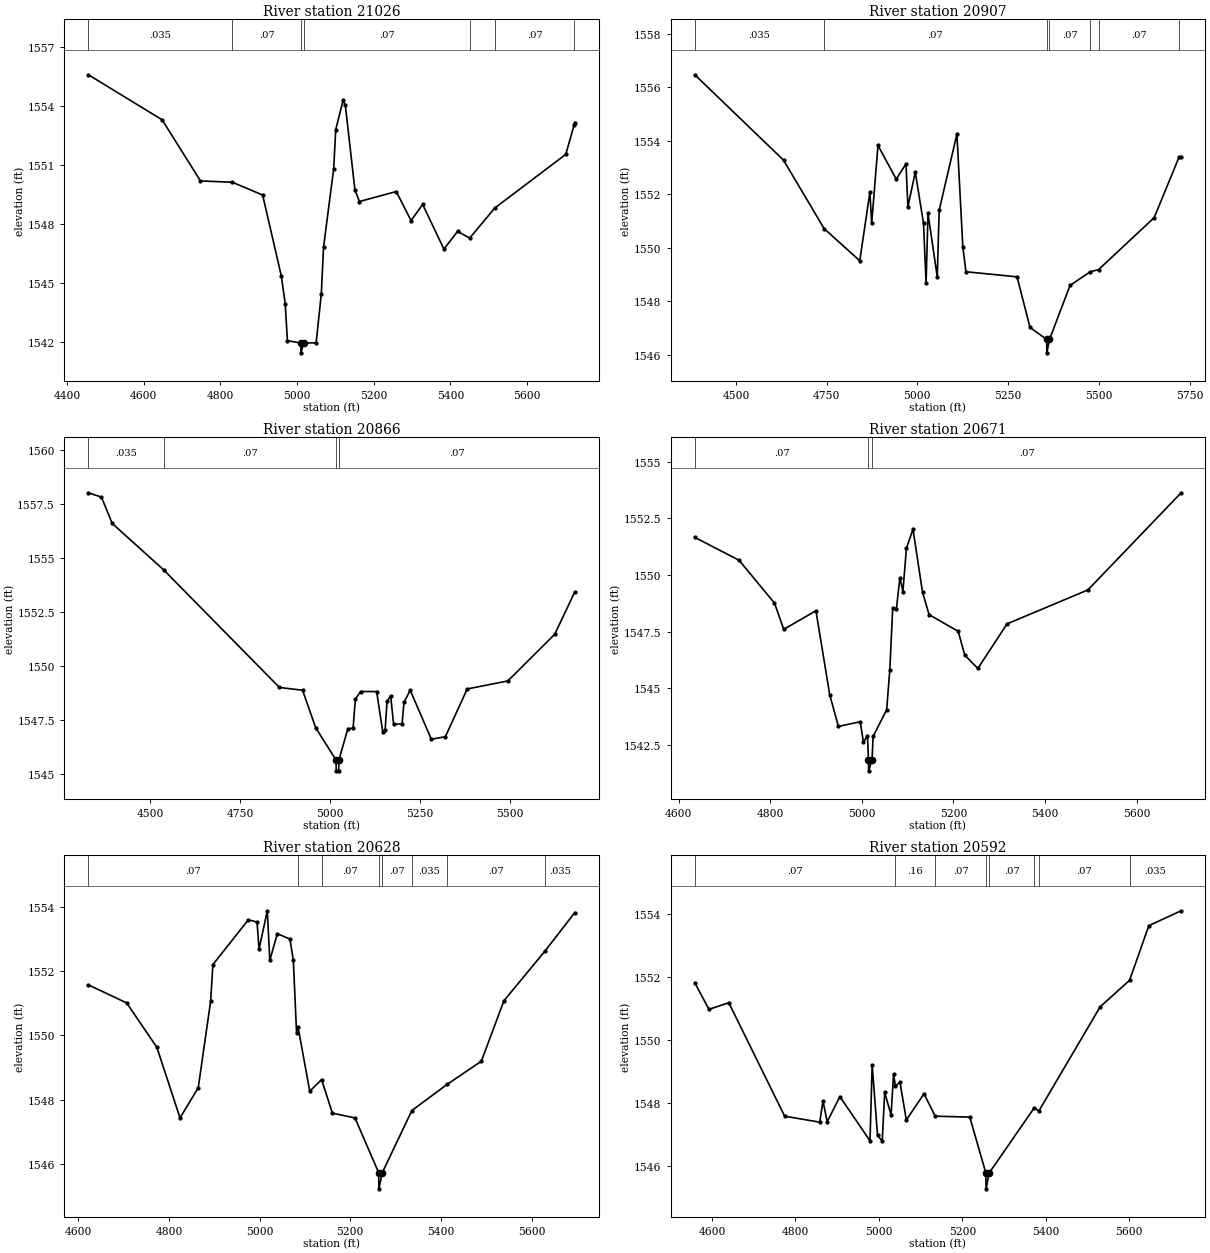
Type RM Length L Ch R = 1,21026,119,119,119
BEGIN DESCRIPTION:
Mapping XS 90fdc292
END DESCRIPTION:
XS GIS Cut Line= 5
      1615278.00      6983829.93      1615294.42      6983409.59
      1615277.06      6983291.53      1615219.99      6983245.69
      1614991.63      6982631.78
#Sta/Elev= 30
  4455.8 1555.61  4647.9 1553.32  4748.0 1550.21  4831.3 1550.14  4910.2 1549.49
  4958.9 1545.37  4969.0 1543.97  4974.8 1542.08  5009.6 1541.96  5010.1 1541.46
  5017.4 1541.96  5049.7 1541.97  5063.1 1544.45  5069.0 1546.84  5095.4 1550.82
  5100.8 1552.82  5119.9 1554.31  5125.8 1554.07  5150.8 1549.75  5162.6 1549.16
  5258.6 1549.67  5297.2 1548.19  5327.5 1549.01  5382.9 1546.74  5418.6 1547.64
  5450.2 1547.30  5515.6 1548.83  5700.7 1551.56  5722.6 1553.06  5724.0 1553.18
#Mann=7,-1,0
  4455.8   0.035       0  4831.3    0.07       0  5009.6    0.07       0
  5017.4    0.07       0  5450.2   0.035       0  5515.6    0.07       0
  5722.6   0.035       0
Bank Sta=5009.6,5017.4
Exp/Cntr=0.3,0.1

Type RM Length L Ch R = 1,20907,41,41,41
BEGIN DESCRIPTION:
Mapping XS ce16e97c
END DESCRIPTION:
XS GIS Cut Line= 6
      1615347.45      6983812.49      1615344.77      6983385.28
      1615356.92      6983251.60      1615339.56      6983201.25
      1615240.82      6983165.83      1615023.51      6982584.64
#Sta/Elev= 30
  4386.7 1556.46  4631.2 1553.27  4743.1 1550.71  4841.3 1549.51  4869.1 1552.07
  4874.1 1550.91  4891.5 1553.82  4941.7 1552.56  4968.6 1553.13  4973.9 1551.53
  4994.3 1552.82  5016.9 1550.91  5024.0 1548.67  5029.3 1551.28  5054.8 1548.91
  5060.1 1551.40  5109.0 1554.24  5125.3 1550.02  5133.9 1549.10  5274.7 1548.91
  5310.4 1547.02  5356.3 1546.57  5356.8 1546.07  5364.1 1546.57  5420.8 1548.59
  5476.6 1549.10  5499.4 1549.18  5652.5 1551.12  5721.4 1553.39  5726.8 1553.40
#Mann=7,-1,0
  4386.7   0.035       0  4743.1    0.07       0  5356.3    0.07       0
  5364.1    0.07       0  5476.6   0.035       0  5499.4    0.07       0
  5721.4   0.035       0
Bank Sta=5356.3,5364.1
Exp/Cntr=0.3,0.1

Type RM Length L Ch R = 1,20866,195,195,195
BEGIN DESCRIPTION:
Mapping XS 04dbbb00
END DESCRIPTION:
XS GIS Cut Line= 6
      1615408.21      6983834.28      1615396.85      6983301.95
      1615396.85      6983199.52      1615369.07      6983173.48
      1615292.69      6983114.45      1615062.57      6982576.82
#Sta/Elev= 30
  4327.2 1558.02  4363.5 1557.82  4393.5 1556.60  4536.9 1554.45  4859.1 1549.01
  4923.6 1548.88  4960.3 1547.14  5016.9 1545.65  5017.4 1545.15  5024.2 1545.15
  5024.7 1545.65  5049.8 1547.10  5064.3 1547.12  5070.6 1548.46  5085.1 1548.82
  5129.9 1548.82  5147.2 1546.93  5153.5 1547.02  5158.9 1548.37  5169.0 1548.62
  5177.1 1547.31  5200.7 1547.32  5206.1 1548.32  5223.4 1548.88  5282.3 1546.61
  5321.3 1546.73  5382.1 1548.94  5495.3 1549.31  5625.8 1551.47  5681.5 1553.42
#Mann=4,-1,0
  4327.2   0.035       0  4536.9    0.07       0  5016.9    0.07       0
  5024.7    0.07       0
Bank Sta=5016.9,5024.7
Exp/Cntr=0.3,0.1

Type RM Length L Ch R = 1,20671,43,43,43
BEGIN DESCRIPTION:
Mapping XS fc65b836
END DESCRIPTION:
XS GIS Cut Line= 6
      1615493.55      6983449.39      1615530.01      6983241.01
      1615533.48      6983135.11      1615531.75      6983089.97
      1615491.82      6983032.68      1615084.59      6982552.26
#Sta/Elev= 30
  4635.0 1551.66  4731.6 1550.65  4809.0 1548.76  4829.3 1547.60  4899.6 1548.42
  4929.6 1544.72  4948.6 1543.31  4996.2 1543.52  5003.4 1542.61  5012.2 1542.91
  5014.3 1541.85  5014.8 1541.35  5022.2 1541.85  5024.5 1542.87  5054.1 1544.05
  5061.0 1545.82  5067.3 1548.55  5075.3 1548.49  5083.0 1549.88  5089.5 1549.27
  5097.3 1551.18  5111.6 1552.02  5132.4 1549.24  5146.7 1548.25  5210.4 1547.51
  5224.7 1546.46  5253.3 1545.87  5317.0 1547.84  5493.8 1549.34  5697.3 1553.63
#Mann=3,-1,0
  4635.0    0.07       0  5014.3    0.07       0  5022.2    0.07       0
Bank Sta=5014.3,5022.2
Exp/Cntr=0.3,0.1

Type RM Length L Ch R = 1,20628,36,36,36
BEGIN DESCRIPTION:
Mapping XS b80f5110
END DESCRIPTION:
XS GIS Cut Line= 6
      1615523.07      6983445.88      1615564.73      6983242.75
      1615575.15      6983116.01      1615569.94      6983074.34
      1615545.64      6983022.26      1615159.07      6982514.19
#Sta/Elev= 30
  4622.5 1551.57  4706.9 1551.01  4773.5 1549.63  4824.5 1547.44  4864.7 1548.38
  4892.0 1551.06  4897.0 1552.20  4975.2 1553.59  4994.4 1553.52  4998.8 1552.68
  5017.0 1553.87  5022.5 1552.33  5039.1 1553.16  5067.0 1552.99  5074.4 1552.33
  5081.5 1550.09  5084.7 1550.27  5110.6 1548.27  5136.7 1548.63  5160.5 1547.59
  5210.4 1547.44  5262.6 1545.74  5263.1 1545.24  5270.5 1545.74  5335.8 1547.67
  5413.4 1548.48  5489.0 1549.20  5538.9 1551.08  5629.4 1552.62  5694.9 1553.81
#Mann=8,-1,0
  4622.5    0.07       0  5084.7    0.16       0  5136.7    0.07       0
  5262.6    0.07       0  5270.5    0.07       0  5335.8   0.035       0
  5413.4    0.07       0  5629.4   0.035       0
Bank Sta=5262.6,5270.5
Exp/Cntr=0.3,0.1

Type RM Length L Ch R = 1,20592,250,250,250
BEGIN DESCRIPTION:
Mapping XS dc1855e6
END DESCRIPTION:
XS GIS Cut Line= 5
      1615542.18      6983477.08      1615604.66      6983223.65
      1615618.55      6983131.63      1615595.98      6983048.30
      1615211.53      6982433.41
#Sta/Elev= 30
  4558.8 1551.81  4592.7 1550.97  4640.2 1551.18  4774.1 1547.59  4858.2 1547.40
  4866.0 1548.07  4876.1 1547.41  4906.4 1548.21  4978.7 1546.81  4983.9 1549.21
  4996.8 1546.98  5008.0 1546.80  5013.9 1548.34  5029.2 1547.63  5035.1 1548.91
  5039.8 1548.54  5050.4 1548.67  5065.8 1547.47  5108.2 1548.30  5134.9 1547.59
  5217.9 1547.56  5256.4 1545.79  5256.9 1545.29  5264.3 1545.79  5372.7 1547.86
  5383.3 1547.75  5530.3 1551.05  5600.9 1551.89  5647.1 1553.62  5724.4 1554.09
#Mann=8,-1,0
  4558.8    0.07       0  5039.8    0.16       0  5134.9    0.07       0
  5256.4    0.07       0  5264.3    0.07       0  5372.7   0.035       0
  5383.3    0.07       0  5600.9   0.035       0
Bank Sta=5256.4,5264.3
Exp/Cntr=0.3,0.1

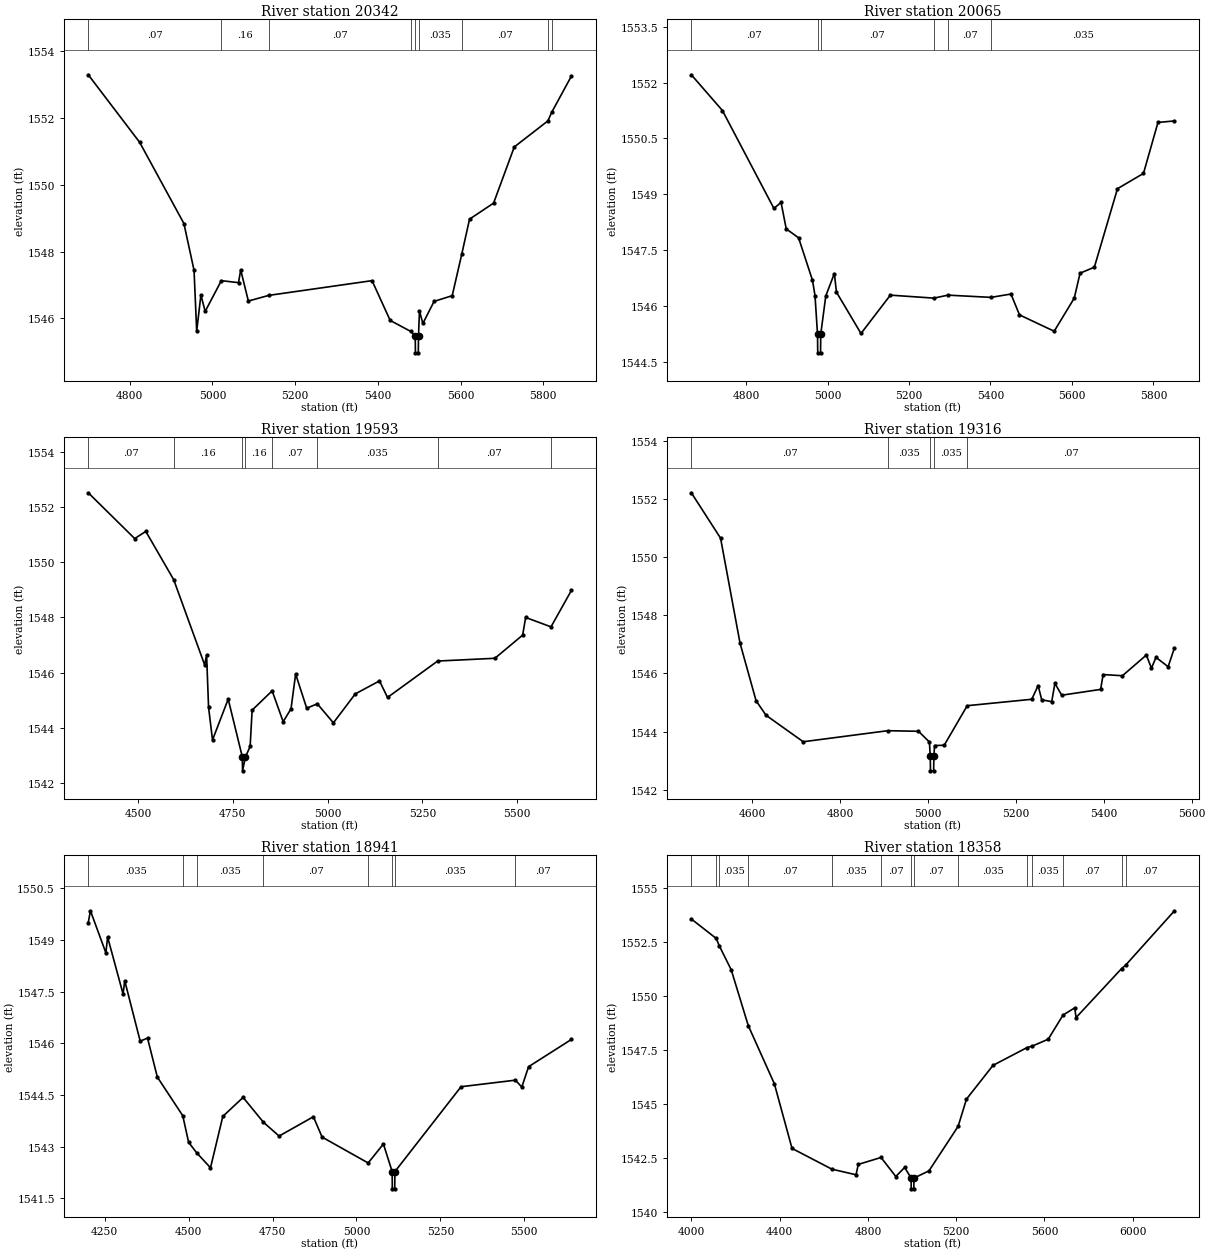
Type RM Length L Ch R = 1,20342,277,277,277
BEGIN DESCRIPTION:
Mapping XS 3bdf1856
END DESCRIPTION:
XS GIS Cut Line= 4
      1615878.96      6983322.93      1615809.53      6983031.29
      1615721.94      6982749.38      1615378.20      6982291.06
#Sta/Elev= 30
  4699.9 1553.29  4824.1 1551.27  4931.1 1548.84  4955.6 1547.44  4962.0 1545.62
  4972.2 1546.70  4982.5 1546.21  5021.6 1547.13  5063.1 1547.07  5068.4 1547.45
  5086.9 1546.52  5136.6 1546.69  5385.9 1547.13  5429.7 1545.94  5479.6 1545.61
  5490.3 1545.47  5490.8 1544.97  5497.7 1544.97  5498.2 1545.47  5500.5 1546.22
  5508.8 1545.85  5535.9 1546.51  5579.7 1546.68  5602.7 1547.92  5621.6 1548.97
  5679.7 1549.45  5729.7 1551.13  5811.0 1551.91  5820.3 1552.17  5867.8 1553.25
#Mann=9,-1,0
  4699.9    0.07       0  5021.6    0.16       0  5136.6    0.07       0
  5479.6   0.035       0  5490.3    0.07       0  5498.2   0.035       0
  5602.7    0.07       0  5811.0   0.035       0  5820.3    0.07       0
Bank Sta=5490.3,5498.2
Exp/Cntr=0.3,0.1

Type RM Length L Ch R = 1,20065,472,472,472
BEGIN DESCRIPTION:
Mapping XS 914a4f13
END DESCRIPTION:
XS GIS Cut Line= 4
      1616080.36      6983218.82      1616035.22      6982890.66
      1615977.93      6982661.50      1615518.51      6982247.20
#Sta/Elev= 30
  4665.6 1552.21  4741.9 1551.25  4868.3 1548.62  4885.9 1548.78  4898.6 1548.07
  4928.9 1547.83  4963.0 1546.69  4969.2 1546.28  4975.4 1545.24  4975.9 1544.74
  4982.8 1544.74  4983.3 1545.24  4995.7 1546.27  5016.7 1546.87  5021.9 1546.37
  5082.1 1545.26  5154.2 1546.29  5261.0 1546.21  5295.6 1546.29  5401.3 1546.23
  5450.3 1546.32  5471.2 1545.76  5556.4 1545.32  5605.7 1546.21  5619.9 1546.88
  5655.0 1547.04  5711.8 1549.15  5775.6 1549.56  5811.2 1550.93  5851.7 1550.97
#Mann=6,-1,0
  4665.6    0.07       0  4975.4    0.07       0  4983.3    0.07       0
  5261.0   0.035       0  5295.6    0.07       0  5401.3   0.035       0
Bank Sta=4975.4,4983.3
Exp/Cntr=0.3,0.1

Type RM Length L Ch R = 1,19593,277,277,277
BEGIN DESCRIPTION:
Mapping XS 92734ad7
END DESCRIPTION:
XS GIS Cut Line= 3
      1616400.84      6983114.62      1616236.77      6982502.61
      1615692.49      6982164.06
#Sta/Elev= 30
  4368.7 1552.52  4491.2 1550.86  4520.5 1551.12  4594.1 1549.37  4675.8 1546.28
  4680.9 1546.64  4686.1 1544.74  4696.5 1543.56  4737.9 1545.04  4775.2 1542.94
  4775.7 1542.44  4783.4 1542.94  4795.8 1543.33  4801.0 1544.64  4853.8 1545.34
  4882.9 1544.22  4903.6 1544.69  4915.8 1545.95  4945.0 1544.71  4973.0 1544.87
  5015.4 1544.18  5073.2 1545.23  5137.0 1545.70  5158.2 1545.10  5290.4 1546.42
  5441.5 1546.52  5514.7 1547.36  5522.6 1548.00  5589.5 1547.66  5643.3 1548.98
#Mann=8,-1,0
  4368.7    0.07       0  4594.1    0.16       0  4775.2   0.035       0
  4783.4    0.16       0  4853.8    0.07       0  4973.0   0.035       0
  5290.4    0.07       0  5589.5   0.035       0
Bank Sta=4775.2,4783.4
Exp/Cntr=0.3,0.1

Type RM Length L Ch R = 1,19316,375,375,375
BEGIN DESCRIPTION:
Mapping XS b5f83d01
END DESCRIPTION:
XS GIS Cut Line= 3
      1616682.07      6982828.12      1616450.31      6982338.55
      1615958.78      6982075.40
#Sta/Elev= 30
  4461.7 1552.21  4528.2 1550.65  4572.5 1547.04  4609.0 1545.06  4631.7 1544.56
  4716.3 1543.65  4908.6 1544.03  4978.5 1544.01  5003.4 1543.64  5005.3 1543.15
  5005.8 1542.65  5013.0 1542.65  5013.5 1543.15  5015.1 1543.52  5037.0 1543.53
  5089.4 1544.89  5236.2 1545.11  5250.7 1545.58  5258.9 1545.09  5281.6 1545.03
  5288.9 1545.66  5304.3 1545.25  5392.9 1545.45  5398.6 1545.96  5442.5 1545.92
  5496.9 1546.63  5508.5 1546.18  5518.9 1546.55  5546.5 1546.23  5560.9 1546.88
#Mann=5,-1,0
  4461.7    0.07       0  4908.6   0.035       0  5005.3   0.035       0
  5013.5   0.035       0  5089.4    0.07       0
Bank Sta=5005.3,5013.5
Exp/Cntr=0.3,0.1

Type RM Length L Ch R = 1,18941,583,583,583
BEGIN DESCRIPTION:
Mapping XS 483913aa
END DESCRIPTION:
XS GIS Cut Line= 3
      1616840.93      6982841.12      1616684.84      6982057.62
      1616048.05      6981991.60
#Sta/Elev= 30
  4201.1 1549.50  4207.6 1549.84  4253.6 1548.62  4258.7 1549.08  4304.7 1547.43
  4309.8 1547.81  4355.8 1546.06  4377.6 1546.15  4406.8 1545.02  4482.6 1543.90
  4500.0 1543.13  4523.6 1542.83  4565.2 1542.39  4601.9 1543.88  4662.3 1544.43
  4722.9 1543.71  4769.5 1543.31  4871.7 1543.87  4897.6 1543.28  5034.8 1542.53
  5080.3 1543.08  5106.3 1542.28  5106.8 1541.78  5114.0 1541.78  5114.5 1542.28
  5311.5 1544.74  5473.4 1544.93  5492.5 1544.73  5512.6 1545.32  5640.2 1546.11
#Mann=8,-1,0
  4201.1   0.035       0  4482.6    0.07       0  4523.6   0.035       0
  4722.9    0.07       0  5034.8   0.035       0  5106.3    0.07       0
  5114.5   0.035       0  5473.4    0.07       0
Bank Sta=5106.3,5114.5
Exp/Cntr=0.3,0.1

Type RM Length L Ch R = 1,18358,869,869,869
BEGIN DESCRIPTION:
Mapping XS d8b441be
END DESCRIPTION:
XS GIS Cut Line= 3
      1617142.98      6983264.06      1617182.04      6982261.47
      1617242.80      6981076.58
#Sta/Elev= 30
  3999.6 1553.56  4112.5 1552.66  4126.2 1552.32  4180.4 1551.21  4257.6 1548.63
  4375.9 1545.94  4456.0 1542.95  4636.6 1541.99  4746.2 1541.73  4756.2 1542.21
  4859.4 1542.53  4926.4 1541.65  4966.4 1542.07  4995.8 1541.58  4996.3 1541.08
  5008.1 1541.08  5008.6 1541.58  5076.5 1541.91  5208.8 1543.97  5246.7 1545.23
  5366.9 1546.79  5520.5 1547.61  5544.3 1547.68  5617.2 1548.00  5684.5 1549.12
  5737.4 1549.45  5743.3 1549.00  5950.1 1551.27  5967.6 1551.42  6189.4 1553.94
#Mann=14,-1,0
  3999.6   0.035       0  4112.5    0.07       0  4126.2   0.035       0
  4257.6    0.07       0  4636.6   0.035       0  4859.4    0.07       0
  4995.8    0.07       0  5008.6    0.07       0  5208.8   0.035       0
  5520.5    0.07       0  5544.3   0.035       0  5684.5    0.07       0
  5950.1   0.035       0  5967.6    0.07       0
Bank Sta=4995.8,5008.6
Exp/Cntr=0.3,0.1