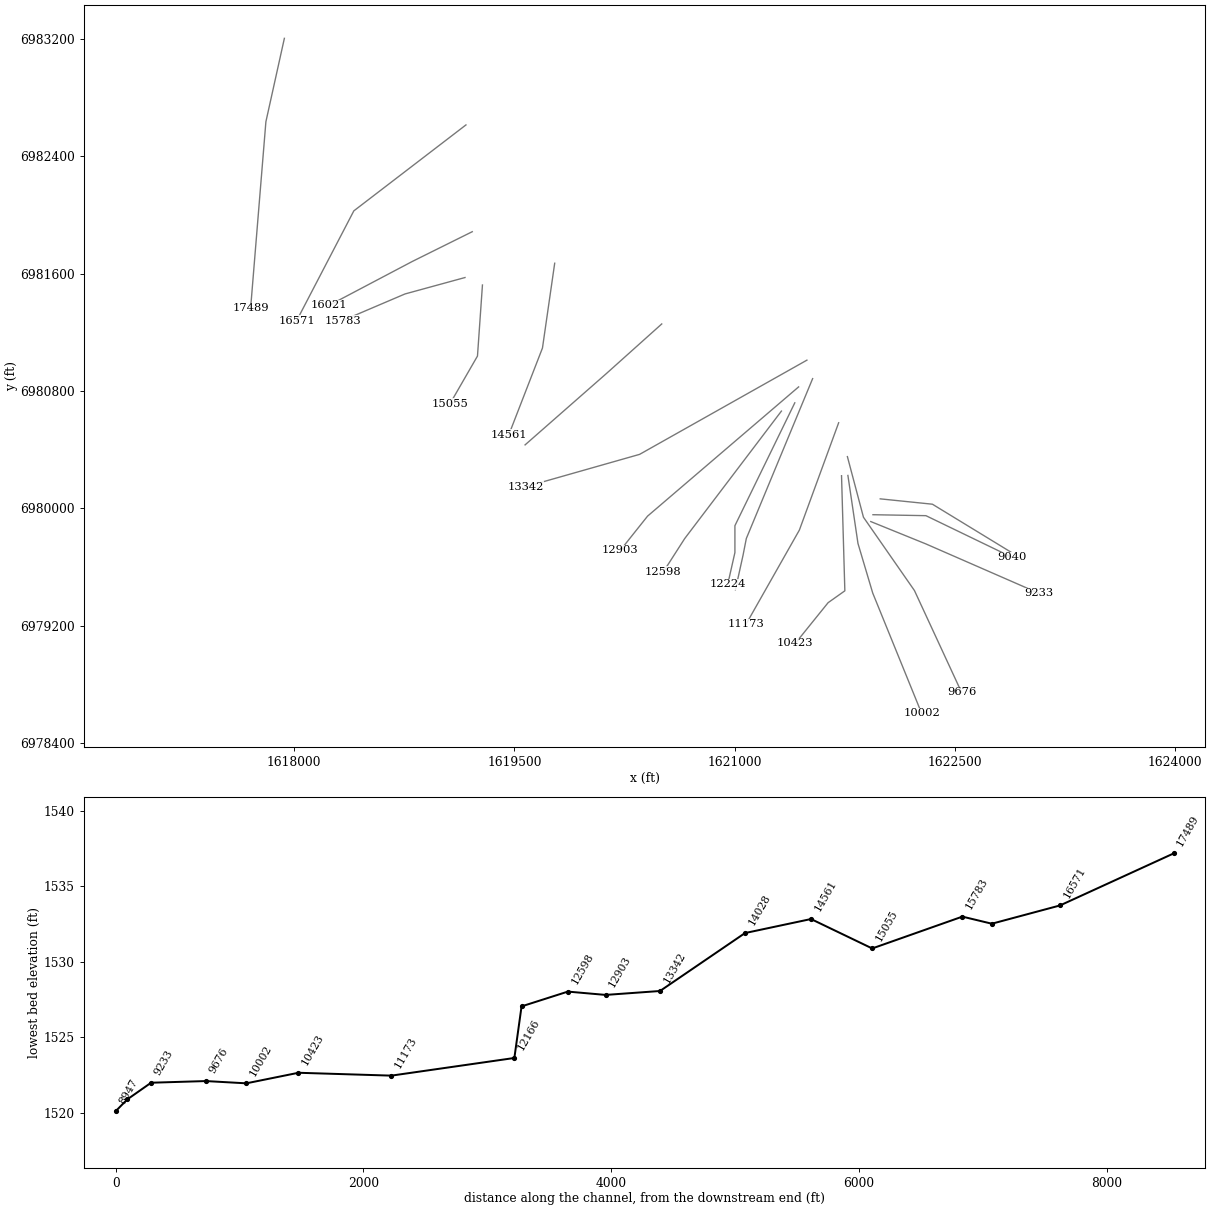
HEC-RAS study Post Oak Creek.prj: Post Oak Creek Base Level Engineering

--- Post Oak Creek.g01 (geometry) --- (continued)

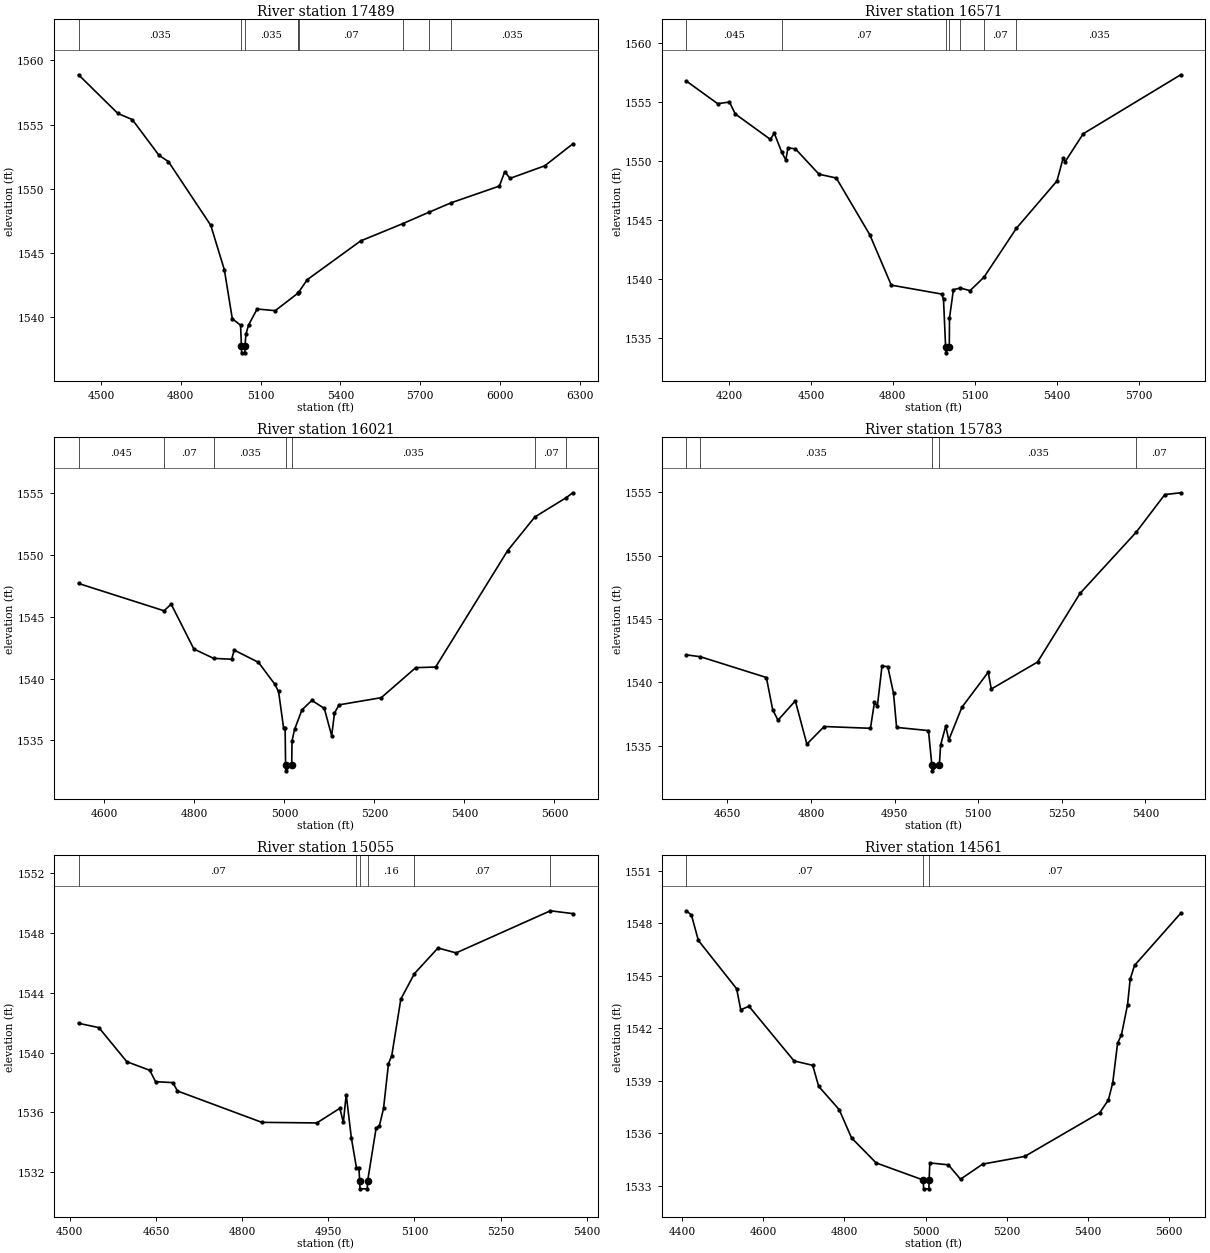
Type RM Length L Ch R = 1,17489,918,918,918
BEGIN DESCRIPTION:
Mapping XS 95796bdd
END DESCRIPTION:
XS GIS Cut Line= 3
      1617932.90      6983203.27      1617807.04      6982634.73
      1617702.87      6981363.00
#Sta/Elev= 30
  4415.7 1558.88  4563.6 1555.86  4617.5 1555.39  4718.1 1552.60  4753.5 1552.11
  4912.7 1547.14  4963.9 1543.67  4993.8 1539.84  5024.8 1539.35  5028.2 1537.69
  5028.7 1537.19  5041.0 1537.19  5041.5 1537.69  5044.9 1538.63  5054.9 1539.36
  5087.1 1540.61  5155.3 1540.48  5239.0 1541.82  5240.1 1541.85  5243.6 1541.93
  5275.7 1542.90  5476.3 1545.92  5633.8 1547.26  5732.3 1548.15  5817.3 1548.90
  5998.1 1550.20  6018.1 1551.32  6038.2 1550.80  6168.6 1551.78  6274.0 1553.49
#Mann=9,-1,0
  4415.7   0.035       0  5028.2   0.035       0  5041.5   0.035       0
  5239.0    0.07       0  5240.1   0.035       0  5243.6    0.07       0
  5633.8   0.035       0  5732.3    0.07       0  5817.3   0.035       0
Bank Sta=5028.2,5041.5
Exp/Cntr=0.3,0.1

Type RM Length L Ch R = 1,16571,550,550,550
BEGIN DESCRIPTION:
Mapping XS a38c1cdf
END DESCRIPTION:
XS GIS Cut Line= 3
      1619169.91      6982613.05      1618406.00      6982027.09
      1618015.35      6981276.19
#Sta/Elev= 30
  4044.5 1556.77  4158.7 1554.86  4201.9 1555.00  4223.1 1553.99  4351.8 1551.83
  4365.8 1552.36  4393.6 1550.73  4408.0 1550.09  4416.2 1551.12  4443.3 1551.03
  4529.6 1548.88  4592.9 1548.56  4715.3 1543.76  4794.2 1539.48  4979.1 1538.72
  4985.4 1538.28  4993.1 1534.24  4993.6 1533.74  5006.6 1534.24  5007.3 1536.69
  5021.7 1539.09  5046.7 1539.24  5082.4 1539.01  5133.8 1540.16  5252.0 1544.29
  5400.8 1548.31  5423.3 1550.25  5430.4 1549.93  5496.8 1552.31  5853.7 1557.31
#Mann=7,-1,0
  4044.5   0.045       0  4393.6    0.07       0  4993.1    0.07       0
  5006.6    0.07       0  5046.7   0.035       0  5133.8    0.07       0
  5252.0   0.035       0
Bank Sta=4993.1,5006.6
Exp/Cntr=0.3,0.1

Type RM Length L Ch R = 1,16021,238,238,238
BEGIN DESCRIPTION:
Mapping XS f79eea15
END DESCRIPTION:
XS GIS Cut Line= 3
      1619212.88      6981885.18      1618804.00      6981682.04
      1618236.75      6981382.80
#Sta/Elev= 30
  4542.8 1547.69  4732.8 1545.48  4748.5 1546.02  4798.9 1542.39  4842.9 1541.63
  4882.9 1541.56  4888.5 1542.30  4942.4 1541.31  4978.1 1539.57  4987.1 1538.95
  4998.3 1535.99  5001.6 1535.99  5002.7 1533.03  5003.2 1532.53  5016.3 1533.03
  5017.0 1534.95  5022.6 1535.88  5039.0 1537.46  5061.0 1538.23  5088.7 1537.58
  5105.1 1535.37  5111.3 1537.20  5121.4 1537.87  5215.2 1538.45  5291.9 1540.88
  5336.0 1540.93  5495.8 1550.34  5556.3 1553.07  5626.3 1554.64  5640.7 1555.03
#Mann=7,-1,0
  4542.8   0.045       0  4732.8    0.07       0  4842.9   0.035       0
  5002.7   0.035       0  5016.3   0.035       0  5556.3    0.07       0
  5626.3   0.035       0
Bank Sta=5002.7,5016.3
Exp/Cntr=0.3,0.1

Type RM Length L Ch R = 1,15783,728,728,728
BEGIN DESCRIPTION:
Mapping XS ed98349a
END DESCRIPTION:
XS GIS Cut Line= 3
      1619163.34      6981572.66      1618754.52      6981460.69
      1618328.76      6981278.96
#Sta/Elev= 30
  4576.4 1542.16  4601.5 1542.01  4719.8 1540.37  4731.0 1537.84  4740.6 1537.00
  4771.7 1538.53  4792.4 1535.11  4823.5 1536.50  4906.5 1536.36  4913.7 1538.41
  4918.9 1538.11  4927.2 1541.27  4937.6 1541.23  4947.9 1539.13  4953.4 1536.43
  5010.6 1536.18  5016.6 1533.50  5017.1 1533.00  5030.2 1533.50  5032.4 1535.04
  5041.6 1536.54  5047.0 1535.43  5070.6 1538.02  5117.8 1540.79  5123.3 1539.46
  5206.3 1541.59  5282.5 1547.01  5383.4 1551.85  5434.7 1554.82  5463.2 1554.96
#Mann=5,-1,0
  4576.4    0.07       0  4601.5   0.035       0  5016.6   0.035       0
  5030.2   0.035       0  5383.4    0.07       0
Bank Sta=5016.6,5030.2
Exp/Cntr=0.3,0.1

Type RM Length L Ch R = 1,15055,494,494,494
BEGIN DESCRIPTION:
Mapping XS 98c083b2
END DESCRIPTION:
XS GIS Cut Line= 3
      1619282.22      6981521.76      1619248.37      6981037.44
      1619061.20      6980712.49
#Sta/Elev= 30
  4515.3 1541.97  4550.7 1541.68  4599.3 1539.40  4639.4 1538.82  4649.4 1538.06
  4679.5 1538.00  4687.5 1537.44  4834.4 1535.34  4930.1 1535.30  4970.2 1536.28
  4976.3 1535.34  4981.3 1537.20  4990.2 1534.31  4999.1 1532.31  5003.4 1532.31
  5004.8 1531.39  5005.3 1530.89  5018.0 1530.89  5018.5 1531.39  5033.3 1534.94
  5039.1 1535.11  5046.3 1536.27  5054.9 1539.27  5060.6 1539.80  5076.4 1543.59
  5100.0 1545.29  5141.1 1547.01  5172.7 1546.68  5336.8 1549.50  5375.8 1549.31
#Mann=6,-1,0
  4515.3    0.07       0  4999.1    0.16       0  5004.8    0.07       0
  5018.5    0.16       0  5100.0    0.07       0  5336.8   0.035       0
Bank Sta=5004.8,5018.5
Exp/Cntr=0.3,0.1

Type RM Length L Ch R = 1,14561,533,533,533
BEGIN DESCRIPTION:
Mapping XS b01346a4
END DESCRIPTION:
XS GIS Cut Line= 3
      1619774.41      6981670.20      1619691.08      6981092.12
      1619462.30      6980501.97
#Sta/Elev= 30
  4411.3 1548.71  4423.6 1548.46  4440.5 1547.02  4534.8 1544.26  4544.9 1543.06
  4565.1 1543.26  4676.2 1540.14  4722.1 1539.89  4736.8 1538.69  4787.4 1537.36
  4817.7 1535.75  4878.3 1534.32  4994.6 1533.34  4995.1 1532.84  5008.3 1532.84
  5008.8 1533.34  5010.5 1534.32  5056.2 1534.21  5086.1 1533.39  5140.6 1534.25
  5244.2 1534.69  5428.8 1537.18  5450.2 1537.91  5461.0 1538.90  5472.9 1541.16
  5482.4 1541.63  5497.4 1543.35  5503.9 1544.81  5514.6 1545.59  5628.3 1548.57
#Mann=3,-1,0
  4411.3    0.07       0  4994.6    0.07       0  5008.8    0.07       0
Bank Sta=4994.6,5008.8
Exp/Cntr=0.3,0.1

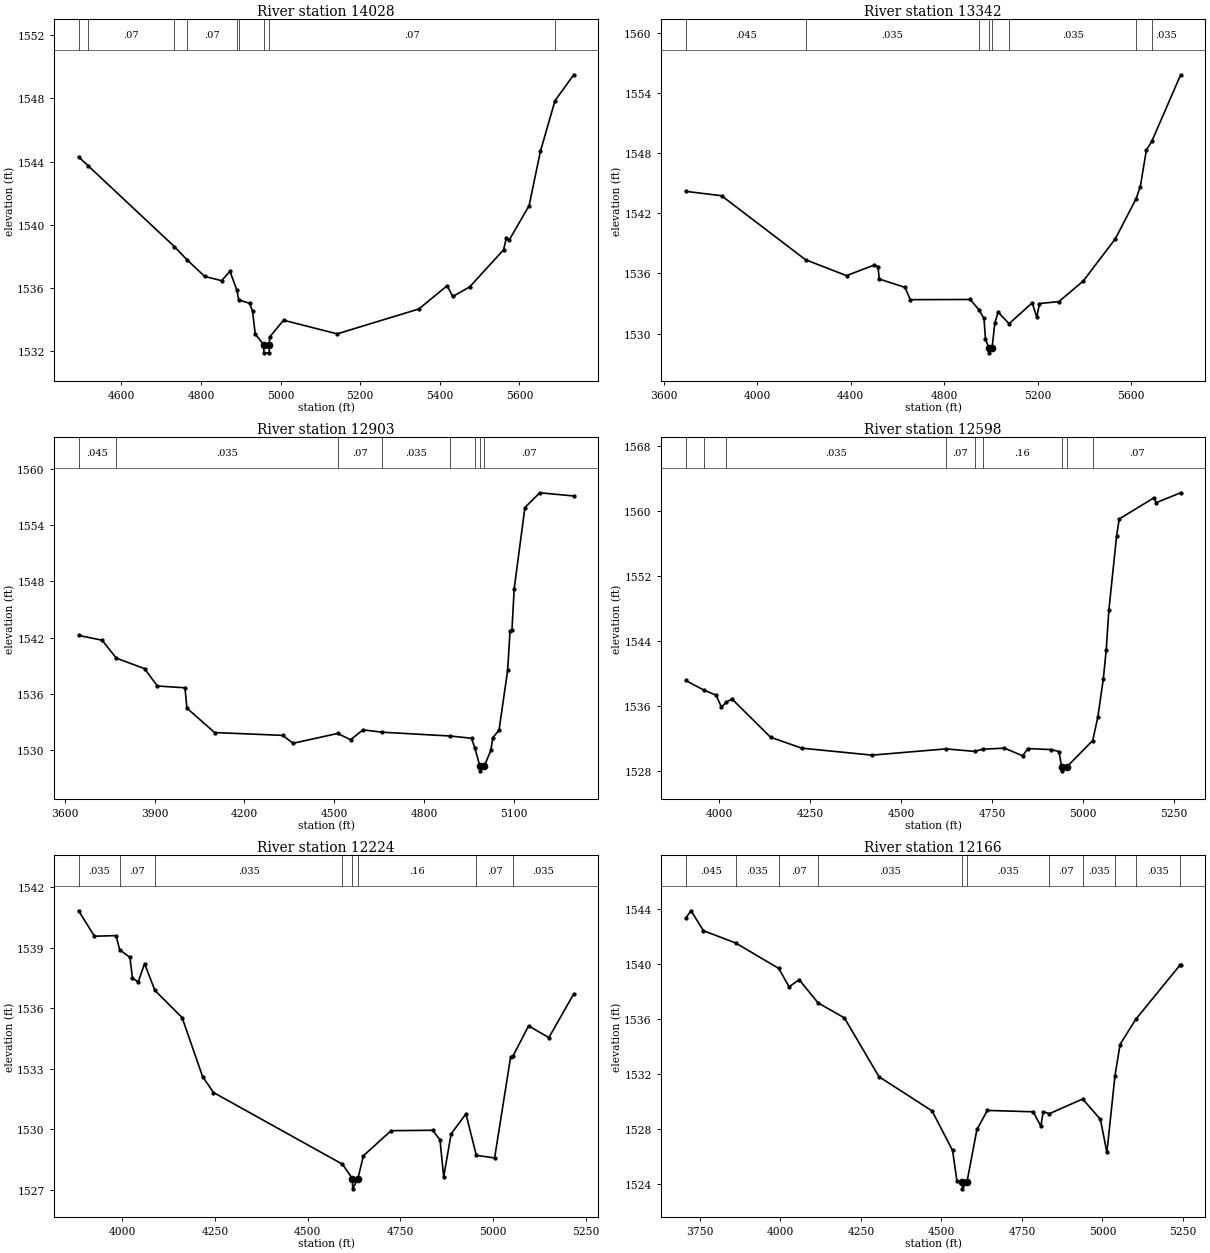
Type RM Length L Ch R = 1,14028,686,686,686
BEGIN DESCRIPTION:
Mapping XS c062f7dc
END DESCRIPTION:
XS GIS Cut Line= 3
      1620503.62      6981256.22      1620125.98      6980917.64
      1619572.65      6980431.86
#Sta/Elev= 30
  4492.8 1544.29  4517.2 1543.72  4733.5 1538.62  4765.4 1537.78  4809.4 1536.74
  4852.0 1536.47  4872.9 1537.06  4890.5 1535.86  4895.1 1535.25  4922.3 1535.04
  4929.7 1534.53  4936.5 1533.10  4957.8 1532.41  4958.3 1531.91  4971.5 1531.91
  4972.0 1532.41  4972.4 1532.90  5007.5 1533.97  5142.2 1533.11  5347.3 1534.68
  5418.4 1536.15  5432.6 1535.47  5475.3 1536.08  5560.2 1538.42  5567.3 1539.19
  5574.0 1539.02  5624.3 1541.21  5652.7 1544.64  5689.3 1547.84  5736.3 1549.48
#Mann=9,-1,0
  4492.8   0.035       0  4517.2    0.07       0  4733.5   0.035       0
  4765.4    0.07       0  4890.5   0.035       0  4895.1    0.07       0
  4957.8    0.07       0  4972.0    0.07       0  5689.3   0.035       0
Bank Sta=4957.8,4972
Exp/Cntr=0.3,0.1

Type RM Length L Ch R = 1,13342,439,439,439
BEGIN DESCRIPTION:
Mapping XS fa334204
END DESCRIPTION:
XS GIS Cut Line= 3
      1621492.53      6981009.46      1620352.89      6980367.25
      1619574.11      6980145.74
#Sta/Elev= 30
  3694.4 1544.20  3848.3 1543.76  4207.4 1537.37  4382.9 1535.78  4501.4 1536.84
  4517.3 1536.69  4523.0 1535.44  4632.8 1534.61  4655.8 1533.38  4911.7 1533.40
  4949.0 1532.38  4970.9 1531.50  4977.1 1529.49  4991.3 1528.57  4991.8 1528.07
  5005.6 1528.57  5017.0 1531.02  5031.5 1532.14  5078.2 1530.98  5177.1 1533.06
  5196.8 1531.63  5208.3 1532.99  5291.4 1533.19  5395.4 1535.24  5532.8 1539.46
  5621.7 1543.47  5639.6 1544.68  5665.7 1548.34  5688.8 1549.20  5812.2 1555.84
#Mann=8,-1,0
  3694.4   0.045       0  4207.4   0.035       0  4949.0    0.16       0
  4991.3    0.07       0  5005.6    0.16       0  5078.2   0.035       0
  5621.7    0.07       0  5688.8   0.035       0
Bank Sta=4991.3,5005.6
Exp/Cntr=0.3,0.1

Type RM Length L Ch R = 1,12903,305,305,305
BEGIN DESCRIPTION:
Mapping XS b4e40384
END DESCRIPTION:
XS GIS Cut Line= 3
      1621436.09      6980827.17      1620407.14      6979946.25
      1620220.96      6979712.45
#Sta/Elev= 30
  3646.4 1542.24  3725.0 1541.73  3772.2 1539.82  3866.6 1538.70  3909.4 1536.85
  4001.6 1536.66  4008.2 1534.49  4100.4 1531.89  4327.6 1531.59  4362.7 1530.75
  4511.2 1531.79  4554.8 1531.13  4596.5 1532.18  4658.8 1531.93  4887.7 1531.52
  4958.7 1531.28  4970.0 1530.22  4986.6 1528.31  4987.1 1527.81  5001.1 1528.31
  5023.2 1529.99  5029.5 1531.34  5050.4 1532.13  5079.2 1538.51  5087.2 1542.69
  5093.6 1542.77  5101.0 1547.19  5136.9 1555.87  5186.5 1557.44  5299.8 1557.10
#Mann=8,-1,0
  3646.4   0.045       0  3772.2   0.035       0  4511.2    0.07       0
  4658.8   0.035       0  4887.7    0.16       0  4970.0    0.07       0
  4986.6    0.07       0  5001.1    0.07       0
Bank Sta=4986.6,5001.1
Exp/Cntr=0.3,0.1

Type RM Length L Ch R = 1,12598,374,374,374
BEGIN DESCRIPTION:
Mapping XS a88d0811
END DESCRIPTION:
XS GIS Cut Line= 3
      1621318.87      6980662.20      1620660.06      6979793.30
      1620514.22      6979565.85
#Sta/Elev= 30
  3906.9 1539.15  3956.9 1537.96  3990.8 1537.34  4005.3 1535.86  4019.3 1536.48
  4034.4 1536.87  4140.5 1532.16  4225.9 1530.82  4419.3 1529.96  4622.5 1530.73
  4701.3 1530.42  4723.4 1530.69  4783.3 1530.82  4833.2 1529.88  4847.8 1530.77
  4912.3 1530.64  4933.1 1530.40  4940.4 1528.53  4940.9 1528.03  4954.9 1528.53
  5025.8 1531.76  5039.8 1534.62  5055.0 1539.35  5063.0 1542.94  5070.2 1547.81
  5091.4 1556.86  5098.6 1559.00  5193.7 1561.59  5200.4 1561.01  5267.5 1562.22
#Mann=9,-1,0
  3906.9   0.035       0  3956.9    0.07       0  4019.3   0.035       0
  4622.5    0.07       0  4701.3   0.035       0  4723.4    0.16       0
  4940.4    0.07       0  4954.9    0.16       0  5025.8    0.07       0
Bank Sta=4940.4,4954.9
Exp/Cntr=0.3,0.1

Type RM Length L Ch R = 1,12224,58,58,58
BEGIN DESCRIPTION:
Mapping XS 4459c630
END DESCRIPTION:
XS GIS Cut Line= 4
      1621410.02      6980718.61      1621002.08      6979880.98
      1621002.08      6979697.81      1620953.52      6979482.78
#Sta/Elev= 30
  3882.2 1540.82  3924.9 1539.56  3983.0 1539.59  3993.0 1538.89  4020.6 1538.51
  4027.5 1537.48  4043.1 1537.30  4060.1 1538.20  4087.8 1536.88  4161.4 1535.53
  4216.6 1532.61  4246.0 1531.82  4593.8 1528.27  4620.9 1527.55  4621.4 1527.05
  4635.4 1527.55  4650.4 1528.69  4725.0 1529.93  4836.9 1529.95  4856.9 1529.48
  4866.9 1527.64  4886.9 1529.77  4926.9 1530.76  4954.9 1528.71  5004.2 1528.58
  5047.4 1533.58  5054.5 1533.65  5095.8 1535.12  5150.6 1534.54  5217.5 1536.70
#Mann=8,-1,0
  3882.2   0.035       0  3993.0    0.07       0  4087.8   0.035       0
  4593.8    0.16       0  4620.9    0.07       0  4635.4    0.16       0
  4954.9    0.07       0  5054.5   0.035       0
Bank Sta=4620.9,4635.4
Exp/Cntr=0.3,0.1

Type RM Length L Ch R = 1,12166,993,993,993
BEGIN DESCRIPTION:
Mapping XS 7ddd46a1
END DESCRIPTION:
XS GIS Cut Line= 4
      1621531.57      6980883.60      1621079.73      6979793.41
      1621057.63      6979680.45      1621005.55      6979444.35
#Sta/Elev= 30
  3705.8 1543.29  3722.7 1543.84  3761.4 1542.39  3861.3 1541.50  3995.1 1539.65
  4027.3 1538.31  4058.3 1538.83  4117.5 1537.14  4199.0 1536.05  4306.2 1531.78
  4471.2 1529.29  4534.6 1526.42  4548.2 1524.21  4564.8 1524.13  4565.3 1523.63
  4579.4 1524.13  4610.3 1527.95  4642.8 1529.33  4784.8 1529.23  4808.7 1528.18
  4816.0 1529.24  4834.9 1529.09  4938.5 1530.16  4993.6 1528.68  5013.8 1526.28
  5038.9 1531.86  5054.7 1534.12  5103.0 1535.94  5240.6 1539.89  5242.8 1539.89
#Mann=11,-1,0
  3705.8   0.045       0  3861.3   0.035       0  3995.1    0.07       0
  4117.5   0.035       0  4564.8   0.035       0  4579.4   0.035       0
  4834.9    0.07       0  4938.5   0.035       0  5038.9    0.07       0
  5103.0   0.035       0  5240.6    0.07       0
Bank Sta=4564.8,4579.4
Exp/Cntr=0.3,0.1

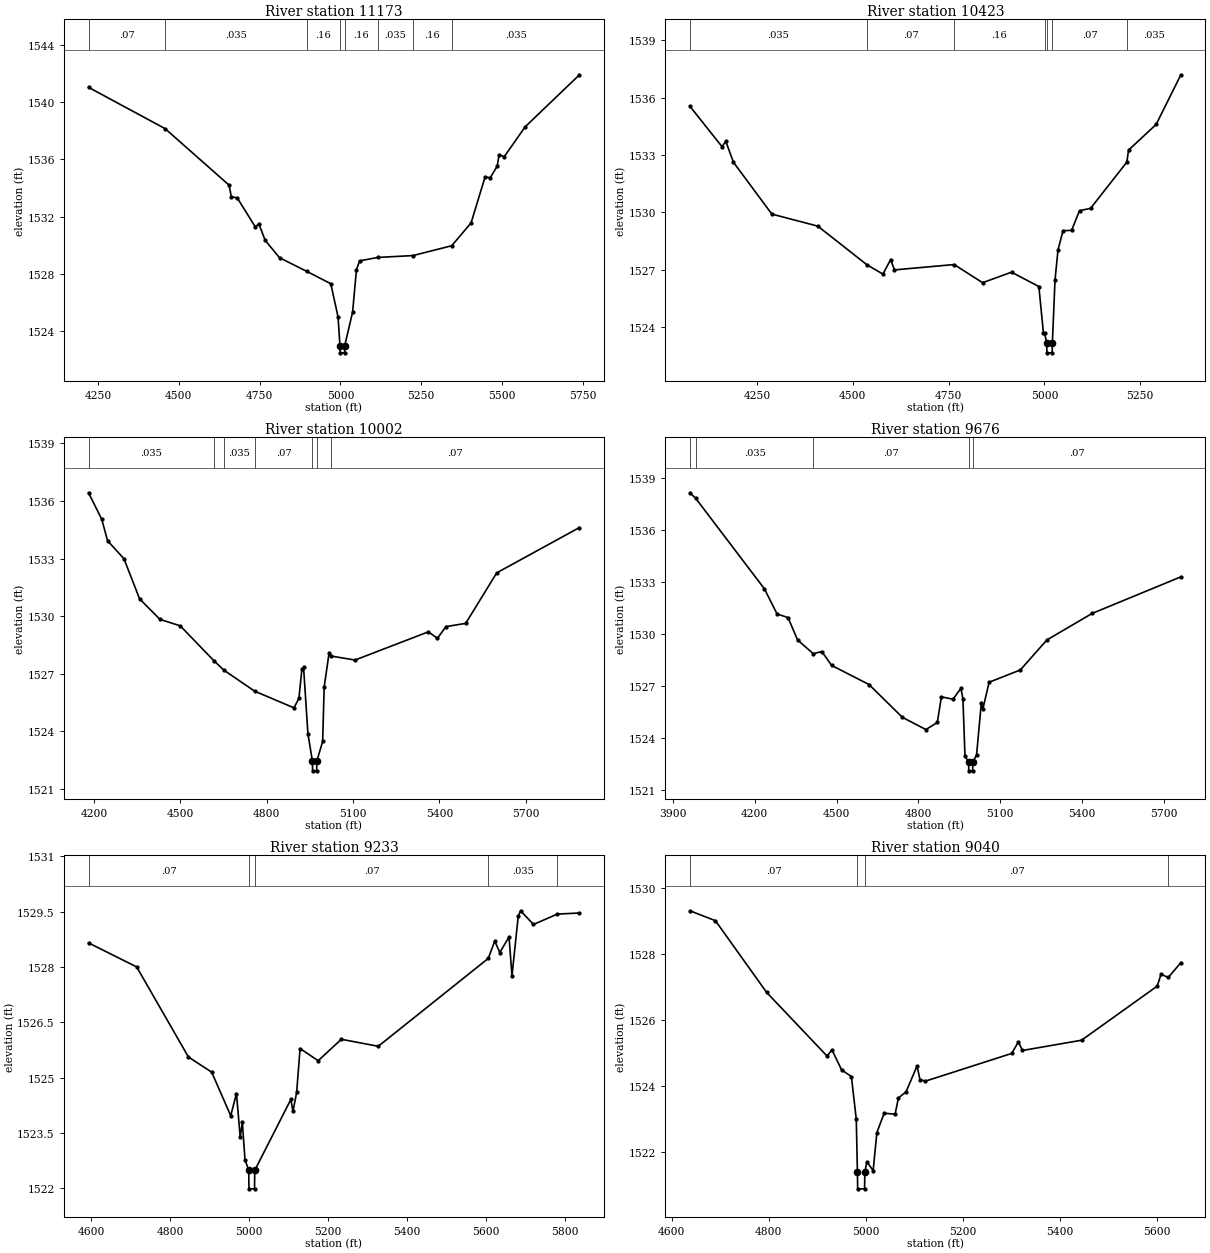
Type RM Length L Ch R = 1,11173,750,750,750
BEGIN DESCRIPTION:
Mapping XS f630e44b
END DESCRIPTION:
XS GIS Cut Line= 3
      1621708.84      6980582.81      1621441.27      6979851.21
      1621076.85      6979207.73
#Sta/Elev= 30
  4221.0 1541.05  4457.8 1538.16  4655.8 1534.20  4662.7 1533.39  4681.0 1533.31
  4736.8 1531.28  4747.9 1531.49  4767.3 1530.34  4811.8 1529.12  4896.4 1528.16
  4970.4 1527.30  4992.8 1524.97  4998.7 1522.96  4999.2 1522.46  5012.9 1522.46
  5013.4 1522.96  5037.8 1525.31  5049.7 1528.28  5059.4 1528.90  5115.9 1529.14
  5224.4 1529.27  5344.4 1529.96  5404.3 1531.56  5447.6 1534.78  5463.4 1534.72
  5485.1 1535.53  5490.9 1536.34  5506.7 1536.19  5571.7 1538.29  5739.5 1541.93
#Mann=8,-1,0
  4221.0    0.07       0  4457.8   0.035       0  4896.4    0.16       0
  4998.7    0.07       0  5013.4    0.16       0  5115.9   0.035       0
  5224.4    0.16       0  5344.4   0.035       0
Bank Sta=4998.7,5013.4
Exp/Cntr=0.3,0.1

Type RM Length L Ch R = 1,10423,421,421,421
BEGIN DESCRIPTION:
Mapping XS 2361f0fc
END DESCRIPTION:
XS GIS Cut Line= 4
      1621728.41      6980221.66      1621750.98      6979436.99
      1621636.97      6979356.14      1621413.00      6979078.35
#Sta/Elev= 30
  4074.7 1535.55  4158.4 1533.44  4168.4 1533.71  4188.4 1532.62  4288.5 1529.91
  4408.5 1529.28  4536.6 1527.26  4578.6 1526.77  4598.6 1527.53  4608.6 1526.99
  4764.5 1527.27  4838.7 1526.32  4914.2 1526.87  4985.6 1526.12  4997.6 1523.67
  5000.7 1523.67  5006.1 1523.15  5006.6 1522.65  5020.3 1522.65  5020.8 1523.15
  5027.8 1526.47  5035.6 1528.04  5048.7 1529.04  5071.0 1529.06  5091.8 1530.09
  5120.6 1530.21  5215.2 1532.63  5219.8 1533.26  5291.7 1534.60  5356.3 1537.20
#Mann=7,-1,0
  4074.7   0.035       0  4536.6    0.07       0  4764.5    0.16       0
  5000.7    0.07       0  5006.1    0.07       0  5020.8    0.07       0
  5215.2   0.035       0
Bank Sta=5006.1,5020.8
Exp/Cntr=0.3,0.1

Type RM Length L Ch R = 1,10002,326,326,326
BEGIN DESCRIPTION:
Mapping XS d4d1a4b5
END DESCRIPTION:
XS GIS Cut Line= 4
      1621771.81      6980223.47      1621840.45      6979759.66
      1621940.79      6979422.12      1622274.21      6978601.57
#Sta/Elev= 30
  4180.5 1536.43  4226.5 1535.05  4246.7 1533.93  4303.5 1533.00  4357.9 1530.91
  4428.6 1529.84  4499.4 1529.50  4617.3 1527.67  4651.4 1527.19  4757.9 1526.10
  4894.8 1525.23  4911.9 1525.73  4922.3 1527.24  4928.0 1527.35  4943.2 1523.88
  4958.9 1522.45  4959.4 1521.95  4973.5 1521.95  4974.0 1522.45  4994.4 1523.48
  4999.7 1526.31  5016.7 1528.08  5022.7 1527.93  5107.1 1527.72  5362.1 1529.19
  5393.5 1528.85  5423.0 1529.46  5491.7 1529.63  5599.6 1532.26  5887.2 1534.62
#Mann=7,-1,0
  4180.5   0.035       0  4617.3    0.07       0  4651.4   0.035       0
  4757.9    0.07       0  4958.9    0.07       0  4974.0    0.07       0
  5022.7    0.07       0
Bank Sta=4958.9,4974
Exp/Cntr=0.3,0.1

Type RM Length L Ch R = 1,9676,443,443,443
BEGIN DESCRIPTION:
Mapping XS 54649a0e
END DESCRIPTION:
XS GIS Cut Line= 4
      1621768.34      6980351.93      1621877.71      6979938.72
      1622225.09      6979438.93      1622545.62      6978745.97
#Sta/Elev= 30
  3962.2 1538.14  3983.8 1537.81  4235.2 1532.60  4281.6 1531.15  4321.8 1530.94
  4356.8 1529.65  4414.1 1528.86  4445.8 1528.98  4481.6 1528.18  4618.6 1527.08
  4740.8 1525.19  4827.3 1524.48  4869.1 1524.89  4884.0 1526.37  4926.4 1526.23
  4955.6 1526.86  4962.9 1526.25  4970.4 1522.97  4983.8 1522.60  4984.3 1522.10
  4998.5 1522.10  4999.0 1522.60  5012.9 1523.02  5030.3 1526.01  5035.8 1525.65
  5058.8 1527.21  5173.4 1527.92  5270.6 1529.65  5436.6 1531.18  5761.8 1533.29
#Mann=5,-1,0
  3962.2    0.07       0  3983.8   0.035       0  4414.1    0.07       0
  4983.8    0.07       0  4999.0    0.07       0
Bank Sta=4983.8,4999
Exp/Cntr=0.3,0.1

Type RM Length L Ch R = 1,9233,193,193,193
BEGIN DESCRIPTION:
Mapping XS dc2dfc68
END DESCRIPTION:
XS GIS Cut Line= 3
      1621927.61      6979909.14      1622303.22      6979756.64
      1623071.73      6979420.73
#Sta/Elev= 30
  4592.5 1528.65  4714.5 1528.00  4845.7 1525.56  4904.6 1525.15  4952.8 1523.97
  4967.4 1524.57  4976.9 1523.39  4982.3 1523.79  4989.0 1522.78  4998.5 1522.49
  4999.0 1521.99  5013.2 1521.99  5013.7 1522.49  5105.2 1524.41  5110.6 1524.09
  5119.9 1524.60  5128.6 1525.79  5174.4 1525.46  5233.1 1526.04  5326.7 1525.85
  5605.5 1528.23  5621.9 1528.70  5634.7 1528.39  5658.1 1528.81  5665.6 1527.76
  5681.5 1529.38  5687.4 1529.52  5720.1 1529.15  5780.5 1529.43  5836.6 1529.46
#Mann=5,-1,0
  4592.5    0.07       0  4998.5    0.07       0  5013.7    0.07       0
  5605.5   0.035       0  5780.5    0.07       0
Bank Sta=4998.5,5013.7
Exp/Cntr=0.3,0.1

Type RM Length L Ch R = 1,9040,93,93,93
BEGIN DESCRIPTION:
Mapping XS 3a311335
END DESCRIPTION:
XS GIS Cut Line= 3
      1621942.50      6979955.86      1622303.22      6979949.34
      1622888.77      6979666.17
#Sta/Elev= 30
  4637.8 1529.30  4690.3 1529.00  4795.7 1526.83  4920.3 1524.90  4930.3 1525.09
  4950.3 1524.48  4970.4 1524.28  4980.4 1522.99  4982.8 1521.38  4983.3 1520.88
  4997.5 1520.88  4998.0 1521.38  5002.3 1521.70  5015.2 1521.43  5022.8 1522.58
  5037.8 1523.17  5060.4 1523.14  5067.2 1523.63  5083.0 1523.82  5105.6 1524.60
  5111.6 1524.19  5122.6 1524.14  5300.5 1524.98  5314.4 1525.33  5322.7 1525.07
  5444.4 1525.38  5600.4 1527.02  5608.1 1527.38  5623.0 1527.28  5649.0 1527.73
#Mann=4,-1,0
  4637.8    0.07       0  4982.8    0.07       0  4998.0    0.07       0
  5623.0   0.035       0
Bank Sta=4982.8,4998
Exp/Cntr=0.3,0.1

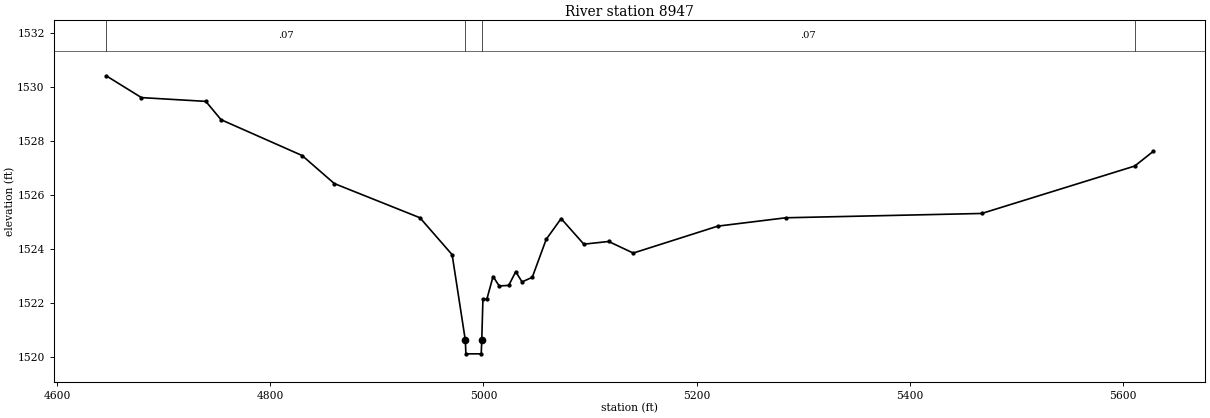
Type RM Length L Ch R = 1,8947,404,404,404
BEGIN DESCRIPTION:
Mapping XS d4b30d5b
END DESCRIPTION:
XS GIS Cut Line= 3
      1621992.03      6980063.93      1622347.49      6980027.47
      1622881.13      6979701.59
#Sta/Elev= 30
  4645.9 1530.42  4679.0 1529.61  4739.4 1529.47  4753.7 1528.79  4829.8 1527.46
  4860.0 1526.42  4940.4 1525.15  4970.6 1523.78  4983.0 1520.60  4983.5 1520.10
  4997.9 1520.10  4998.4 1520.60  4999.5 1522.13  5003.2 1522.13  5009.0 1522.97
  5014.8 1522.62  5023.7 1522.64  5030.3 1523.15  5036.2 1522.77  5045.8 1522.94
  5058.9 1524.35  5072.9 1525.12  5094.2 1524.17  5117.5 1524.27  5140.6 1523.84
  5220.0 1524.84  5283.9 1525.15  5467.7 1525.31  5611.3 1527.07  5628.5 1527.61
#Mann=4,-1,0
  4645.9    0.07       0  4983.0    0.07       0  4998.4    0.07       0
  5611.3   0.035       0
Bank Sta=4983,4998.4
Exp/Cntr=0.3,0.1