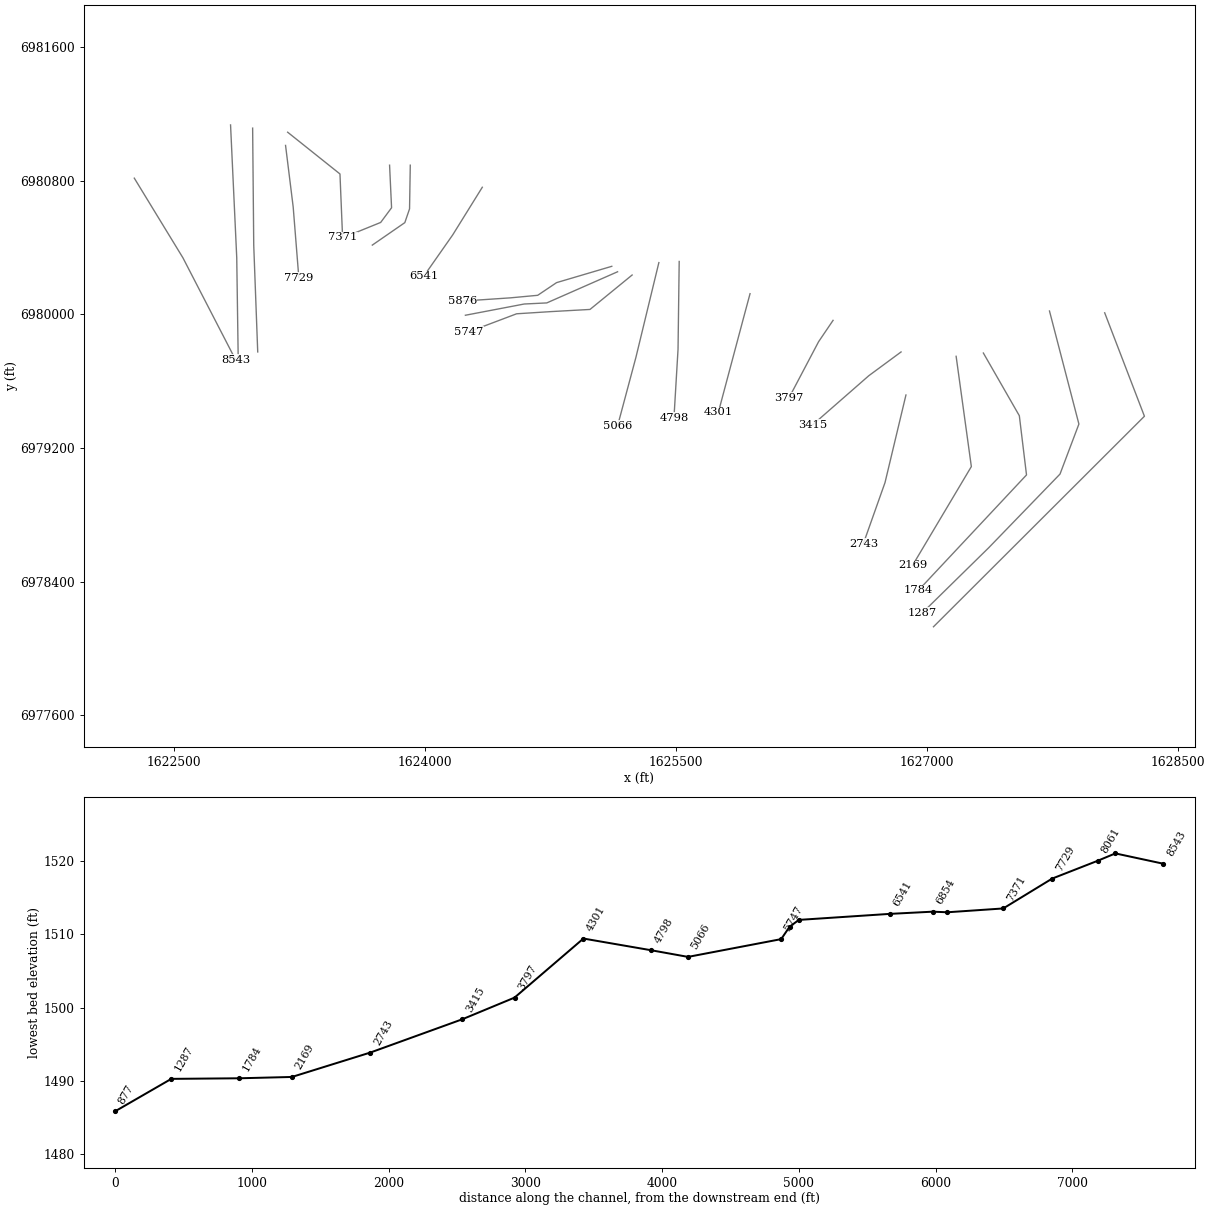
HEC-RAS study Post Oak Creek.prj: Post Oak Creek Base Level Engineering

--- Post Oak Creek.g01 (geometry) --- (continued)

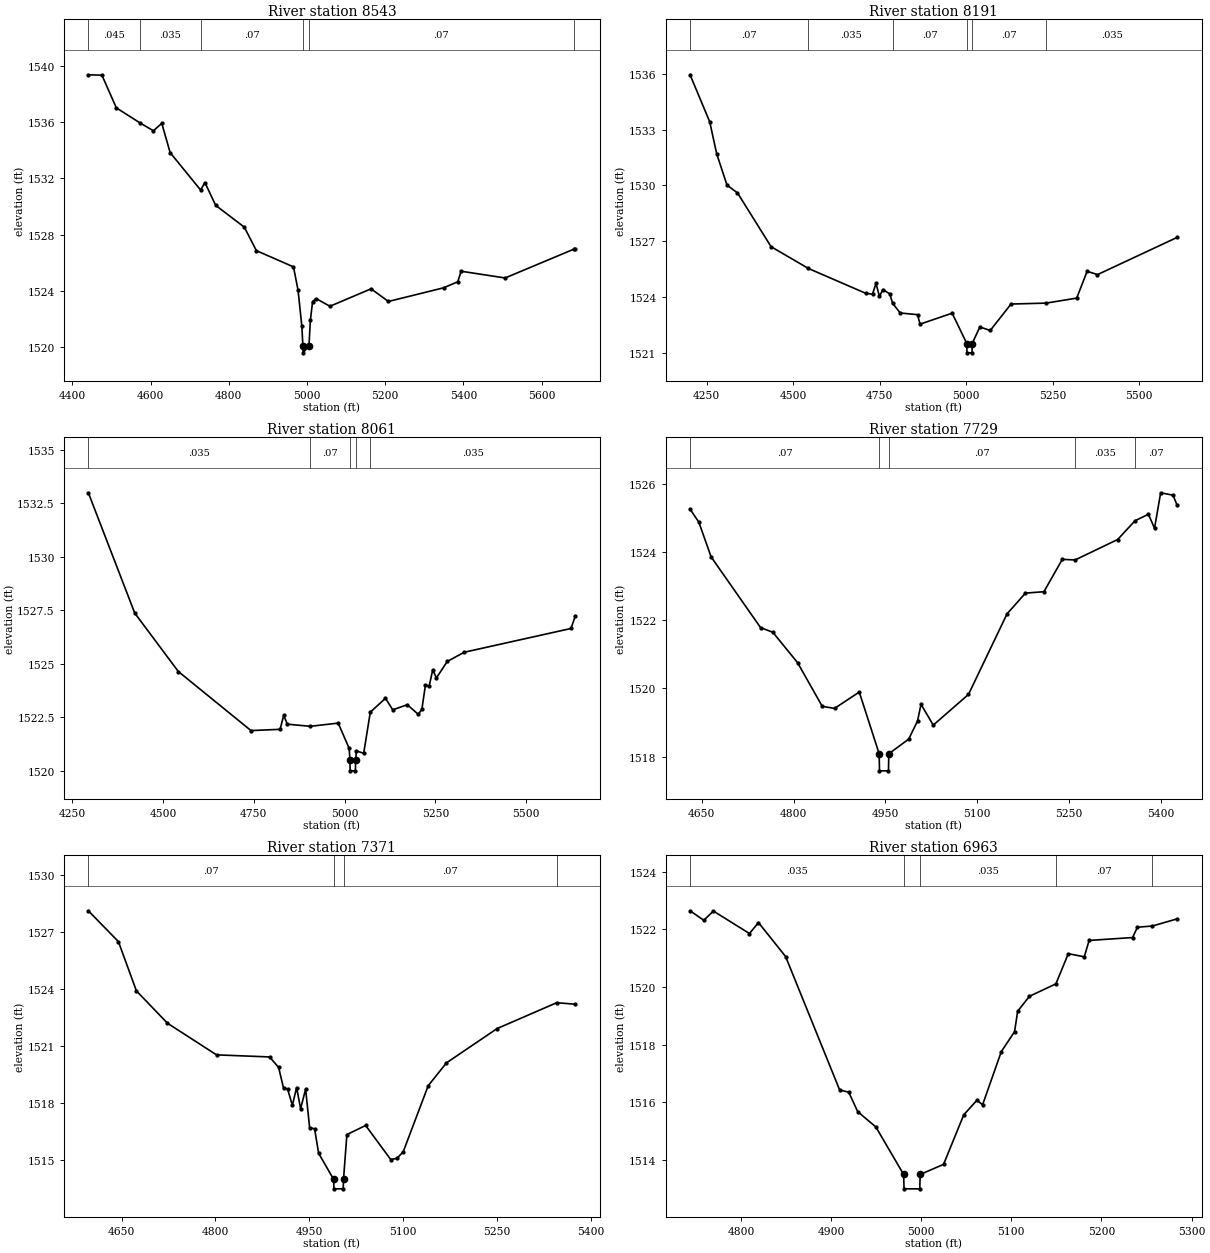
Type RM Length L Ch R = 1,8543,352,352,352
BEGIN DESCRIPTION:
Mapping XS 3b79555e
END DESCRIPTION:
XS GIS Cut Line= 3
      1622263.93      6980816.15      1622554.79      6980338.54
      1622869.29      6979727.98
#Sta/Elev= 30
  4440.8 1539.36  4475.6 1539.33  4512.4 1537.01  4571.8 1535.96  4607.3 1535.38
  4628.7 1535.91  4650.0 1533.83  4728.0 1531.17  4739.0 1531.70  4766.5 1530.08
  4839.8 1528.53  4870.7 1526.86  4965.5 1525.71  4977.3 1524.04  4986.9 1521.49
  4989.6 1520.10  4990.1 1519.60  5005.1 1520.10  5008.8 1521.93  5014.4 1523.24
  5023.1 1523.46  5058.8 1522.91  5164.0 1524.15  5208.3 1523.25  5349.3 1524.22
  5385.7 1524.65  5394.3 1525.40  5506.8 1524.92  5682.0 1526.96  5686.8 1526.99
#Mann=6,-1,0
  4440.8   0.045       0  4571.8   0.035       0  4728.0    0.07       0
  4989.6    0.07       0  5005.1    0.07       0  5682.0   0.035       0
Bank Sta=4989.6,5005.1
Exp/Cntr=0.3,0.1

Type RM Length L Ch R = 1,8191,130,130,130
BEGIN DESCRIPTION:
Mapping XS c57d7b8f
END DESCRIPTION:
XS GIS Cut Line= 3
      1622839.03      6981134.83      1622875.96      6980340.29
      1622884.86      6979727.65
#Sta/Elev= 30
  4201.9 1535.94  4258.8 1533.41  4278.8 1531.70  4308.8 1530.01  4338.9 1529.60
  4436.1 1526.71  4544.0 1525.54  4709.3 1524.21  4729.3 1524.16  4739.3 1524.74
  4749.3 1524.04  4759.3 1524.41  4779.4 1524.17  4787.3 1523.67  4809.4 1523.15
  4859.4 1523.06  4866.7 1522.55  4959.5 1523.14  5001.8 1521.51  5002.3 1521.01
  5016.9 1521.01  5017.4 1521.51  5039.6 1522.40  5069.6 1522.21  5129.6 1523.63
  5231.4 1523.68  5319.6 1523.95  5349.6 1525.39  5379.6 1525.21  5610.0 1527.21
#Mann=6,-1,0
  4201.9    0.07       0  4544.0   0.035       0  4787.3    0.07       0
  5001.8    0.07       0  5017.4    0.07       0  5231.4   0.035       0
Bank Sta=5001.8,5017.4
Exp/Cntr=0.3,0.1

Type RM Length L Ch R = 1,8061,332,332,332
BEGIN DESCRIPTION:
Mapping XS dbcffd42
END DESCRIPTION:
XS GIS Cut Line= 3
      1622970.97      6981115.71      1622977.52      6980414.51
      1623001.35      6979775.49
#Sta/Elev= 30
  4294.8 1532.99  4422.5 1527.37  4542.5 1524.64  4742.5 1521.88  4822.5 1521.94
  4832.5 1522.59  4842.5 1522.18  4905.6 1522.08  4982.5 1522.23  5012.6 1521.05
  5014.8 1520.50  5015.3 1520.00  5029.9 1520.00  5030.4 1520.50  5032.6 1520.93
  5052.6 1520.82  5070.8 1522.74  5112.6 1523.39  5132.6 1522.85  5172.7 1523.09
  5202.7 1522.64  5212.7 1522.87  5222.7 1524.02  5232.7 1523.95  5242.7 1524.72
  5252.7 1524.34  5282.7 1525.11  5329.3 1525.54  5623.0 1526.65  5635.5 1527.25
#Mann=5,-1,0
  4294.8   0.035       0  4905.6    0.07       0  5014.8    0.07       0
  5030.4    0.07       0  5070.8   0.035       0
Bank Sta=5014.8,5030.4
Exp/Cntr=0.3,0.1

Type RM Length L Ch R = 1,7729,358,358,358
BEGIN DESCRIPTION:
Mapping XS 530cf2b6
END DESCRIPTION:
XS GIS Cut Line= 3
      1623167.63      6981012.15      1623213.20      6980643.67
      1623246.90      6980221.10
#Sta/Elev= 30
  4631.0 1525.25  4645.3 1524.87  4665.4 1523.85  4746.0 1521.78  4766.2 1521.64
  4806.5 1520.75  4846.8 1519.47  4866.9 1519.41  4907.2 1519.89  4939.7 1518.08
  4940.2 1517.58  4954.9 1517.58  4955.4 1518.08  4987.9 1518.51  5002.3 1519.04
  5008.0 1519.53  5028.0 1518.92  5085.5 1519.82  5148.4 1522.18  5178.5 1522.79
  5208.6 1522.83  5238.7 1523.78  5259.4 1523.76  5329.0 1524.36  5357.3 1524.91
  5379.2 1525.10  5389.2 1524.69  5399.2 1525.73  5419.3 1525.66  5426.2 1525.36
#Mann=5,-1,0
  4631.0    0.07       0  4939.7    0.07       0  4955.4    0.07       0
  5259.4   0.035       0  5357.3    0.07       0
Bank Sta=4939.7,4955.4
Exp/Cntr=0.3,0.1

Type RM Length L Ch R = 1,7371,408,408,408
BEGIN DESCRIPTION:
Mapping XS 8ce0f762
END DESCRIPTION:
XS GIS Cut Line= 3
      1623180.19      6981091.29      1623492.71      6980841.26
      1623508.32      6980462.72
#Sta/Elev= 30
  4596.7 1528.12  4644.8 1526.50  4673.6 1523.91  4723.3 1522.21  4801.7 1520.55
  4886.6 1520.44  4901.0 1519.89  4909.0 1518.79  4915.4 1518.75  4923.0 1517.90
  4929.8 1518.83  4936.2 1517.72  4944.2 1518.75  4950.6 1516.73  4958.6 1516.66
  4965.0 1515.38  4989.0 1514.01  4989.5 1513.51  5004.3 1513.51  5004.8 1514.01
  5010.2 1516.36  5040.2 1516.84  5080.3 1515.05  5090.3 1515.11  5100.3 1515.46
  5140.3 1518.93  5169.5 1520.13  5250.4 1521.93  5345.8 1523.29  5375.8 1523.21
#Mann=4,-1,0
  4596.7    0.07       0  4989.0    0.07       0  5004.8    0.07       0
  5345.8   0.035       0
Bank Sta=4989,5004.8
Exp/Cntr=0.3,0.1

Type RM Length L Ch R = 1,6963,109,109,109
BEGIN DESCRIPTION:
Mapping XS ba04dfd7
END DESCRIPTION:
XS GIS Cut Line= 4
      1623789.09      6980893.84      1623801.02      6980638.83
      1623735.92      6980550.94      1623573.13      6980484.74
#Sta/Elev= 30
  4743.6 1522.65  4758.8 1522.32  4769.5 1522.64  4809.5 1521.86  4819.5 1522.24
  4849.6 1521.06  4909.6 1516.42  4919.6 1516.35  4929.6 1515.67  4949.7 1515.14
  4980.5 1513.49  4981.0 1512.99  4998.4 1512.99  4998.9 1513.49  5024.8 1513.84
  5047.2 1515.56  5061.9 1516.07  5068.1 1515.91  5088.9 1517.76  5103.6 1518.45
  5107.0 1519.16  5120.1 1519.68  5149.4 1520.11  5163.2 1521.16  5180.9 1521.05
  5186.3 1521.62  5234.5 1521.72  5239.9 1522.08  5256.4 1522.12  5284.0 1522.37
#Mann=5,-1,0
  4743.6   0.035       0  4980.5   0.035       0  4998.9   0.035       0
  5149.4    0.07       0  5256.4   0.035       0
Bank Sta=4980.5,4998.9
Exp/Cntr=0.3,0.1

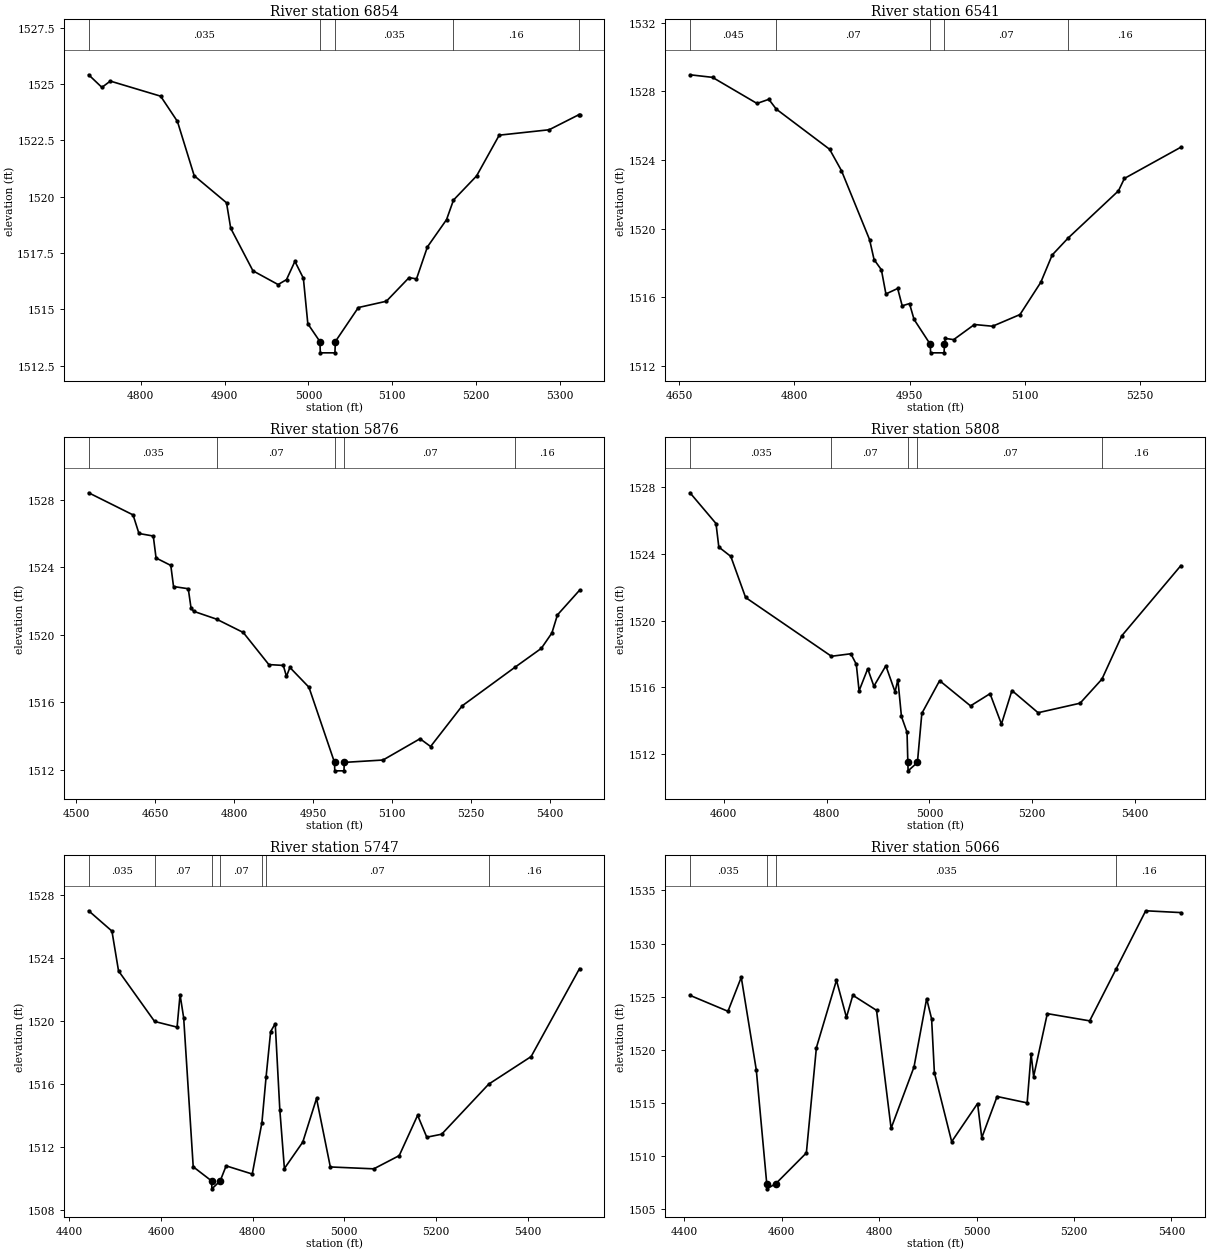
Type RM Length L Ch R = 1,6854,313,313,313
BEGIN DESCRIPTION:
Mapping XS 9a36ce7c
END DESCRIPTION:
XS GIS Cut Line= 4
      1623912.78      6980893.82      1623908.44      6980632.32
      1623880.23      6980549.85      1623685.98      6980415.29
#Sta/Elev= 30
  4738.1 1525.41  4753.9 1524.85  4763.9 1525.13  4823.9 1524.46  4843.9 1523.34
  4863.9 1520.93  4902.4 1519.73  4907.4 1518.60  4933.9 1516.71  4963.9 1516.10
  4973.9 1516.32  4983.9 1517.13  4994.0 1516.38  4999.3 1514.36  5013.7 1513.57
  5014.2 1513.07  5031.6 1513.07  5032.1 1513.57  5059.5 1515.08  5092.9 1515.36
  5120.0 1516.41  5128.8 1516.35  5141.8 1517.77  5164.6 1518.98  5172.9 1519.85
  5200.4 1520.92  5227.4 1522.73  5286.9 1522.97  5322.4 1523.64  5323.1 1523.64
#Mann=5,-1,0
  4738.1   0.035       0  5013.7   0.035       0  5032.1   0.035       0
  5172.9    0.16       0  5322.4   0.035       0
Bank Sta=5013.7,5032.1
Exp/Cntr=0.3,0.1

Type RM Length L Ch R = 1,6541,665,665,665
BEGIN DESCRIPTION:
Mapping XS 56f737d4
END DESCRIPTION:
XS GIS Cut Line= 3
      1624343.12      6980761.64      1624166.24      6980476.25
      1623992.62      6980227.76
#Sta/Elev= 30
  4664.0 1528.97  4693.3 1528.82  4751.2 1527.30  4766.6 1527.54  4776.3 1526.97
  4845.7 1524.63  4861.1 1523.39  4897.7 1519.37  4903.6 1518.20  4913.1 1517.61
  4919.0 1516.20  4934.3 1516.52  4940.2 1515.51  4949.7 1515.64  4955.6 1514.72
  4976.7 1513.27  4977.2 1512.77  4994.7 1512.77  4995.2 1513.27  4996.2 1513.61
  5007.2 1513.54  5034.2 1514.42  5057.8 1514.32  5093.5 1515.00  5120.6 1516.88
  5135.4 1518.47  5156.2 1519.46  5221.7 1522.21  5229.4 1522.93  5302.9 1524.75
#Mann=5,-1,0
  4664.0   0.045       0  4776.3    0.07       0  4976.7    0.07       0
  4995.2    0.07       0  5156.2    0.16       0
Bank Sta=4976.7,4995.2
Exp/Cntr=0.3,0.1

Type RM Length L Ch R = 1,5876,68,68,68
BEGIN DESCRIPTION:
Mapping XS 1c311d13
END DESCRIPTION:
XS GIS Cut Line= 5
      1625116.71      6980288.19      1624786.84      6980190.53
      1624674.00      6980114.58      1624511.24      6980099.38
      1624222.61      6980079.85
#Sta/Elev= 30
  4523.6 1528.41  4608.0 1527.10  4619.2 1526.00  4646.4 1525.85  4651.7 1524.55
  4679.7 1524.11  4684.9 1522.86  4712.9 1522.73  4718.2 1521.58  4723.5 1521.39
  4766.6 1520.93  4817.4 1520.14  4866.0 1518.24  4893.5 1518.19  4899.5 1517.54
  4906.0 1518.07  4942.2 1516.90  4990.8 1512.45  4991.3 1511.95  5008.8 1511.95
  5009.3 1512.45  5083.0 1512.59  5153.3 1513.85  5173.4 1513.39  5233.5 1515.80
  5333.2 1518.07  5383.8 1519.20  5403.9 1520.11  5414.4 1521.18  5456.4 1522.64
#Mann=5,-1,0
  4523.6   0.035       0  4766.6    0.07       0  4990.8    0.07       0
  5009.3    0.07       0  5333.2    0.16       0
Bank Sta=4990.8,5009.3
Exp/Cntr=0.3,0.1

Type RM Length L Ch R = 1,5808,61,61,61
BEGIN DESCRIPTION:
Mapping XS 7f08911b
END DESCRIPTION:
XS GIS Cut Line= 4
      1625151.39      6980255.62      1624728.25      6980069.00
      1624593.70      6980062.49      1624242.15      6979995.22
#Sta/Elev= 30
  4534.1 1527.65  4584.7 1525.81  4590.2 1524.40  4613.5 1523.84  4642.3 1521.38
  4809.3 1517.86  4847.1 1518.01  4857.7 1517.38  4863.1 1515.79  4879.9 1517.11
  4891.9 1516.07  4915.2 1517.29  4933.1 1515.73  4938.6 1516.46  4945.5 1514.26
  4956.4 1513.31  4958.0 1511.50  4958.5 1511.00  4976.6 1511.50  4985.2 1514.44
  5019.8 1516.40  5079.9 1514.89  5117.9 1515.62  5140.1 1513.80  5160.5 1515.81
  5211.4 1514.48  5293.1 1515.05  5335.6 1516.49  5374.3 1519.09  5489.2 1523.29
#Mann=5,-1,0
  4534.1   0.035       0  4809.3    0.07       0  4958.0    0.07       0
  4976.6    0.07       0  5335.6    0.16       0
Bank Sta=4958,4976.6
Exp/Cntr=0.3,0.1

Type RM Length L Ch R = 1,5747,681,681,681
BEGIN DESCRIPTION:
Mapping XS 774d950a
END DESCRIPTION:
XS GIS Cut Line= 5
      1625238.23      6980236.10      1624986.50      6980029.94
      1624752.12      6980016.92      1624548.13      6980003.90
      1624261.71      6979895.41
#Sta/Elev= 30
  4442.4 1526.99  4493.2 1525.70  4507.6 1523.17  4586.3 1519.96  4635.3 1519.60
  4641.8 1521.66  4649.7 1520.19  4670.5 1510.73  4710.7 1509.83  4711.2 1509.33
  4729.3 1509.83  4742.3 1510.79  4799.3 1510.27  4820.4 1513.54  4829.5 1516.45
  4839.4 1519.32  4849.4 1519.82  4859.4 1514.36  4869.4 1510.62  4909.5 1512.30
  4939.5 1515.07  4969.6 1510.72  5064.4 1510.60  5119.9 1511.44  5160.0 1514.00
  5180.0 1512.61  5212.5 1512.80  5315.1 1515.98  5407.6 1517.73  5513.2 1523.32
#Mann=7,-1,0
  4442.4   0.035       0  4586.3    0.07       0  4710.7    0.07       0
  4729.3    0.07       0  4820.4   0.035       0  4829.5    0.07       0
  5315.1    0.16       0
Bank Sta=4710.7,4729.3
Exp/Cntr=0.3,0.1

Type RM Length L Ch R = 1,5066,268,268,268
BEGIN DESCRIPTION:
Mapping XS e57d3d1b
END DESCRIPTION:
XS GIS Cut Line= 3
      1625397.97      6980310.36      1625260.80      6979742.61
      1625151.44      6979332.94
#Sta/Elev= 30
  4411.5 1525.12  4489.5 1523.62  4516.8 1526.82  4547.7 1518.09  4569.1 1507.41
  4569.6 1506.91  4588.0 1507.41  4650.5 1510.29  4671.1 1520.20  4712.3 1526.54
  4732.8 1523.05  4745.9 1525.13  4794.6 1523.71  4824.5 1512.61  4871.5 1518.37
  4897.5 1524.81  4907.7 1522.91  4913.4 1517.85  4948.9 1511.35  5002.1 1514.94
  5010.7 1511.72  5042.2 1515.60  5103.9 1515.00  5112.0 1519.61  5117.2 1517.48
  5145.3 1523.40  5232.3 1522.72  5286.6 1527.60  5347.4 1533.08  5419.6 1532.91
#Mann=4,-1,0
  4411.5   0.035       0  4569.1    0.07       0  4588.0   0.035       0
  5286.6    0.16       0
Bank Sta=4569.1,4588
Exp/Cntr=0.3,0.1

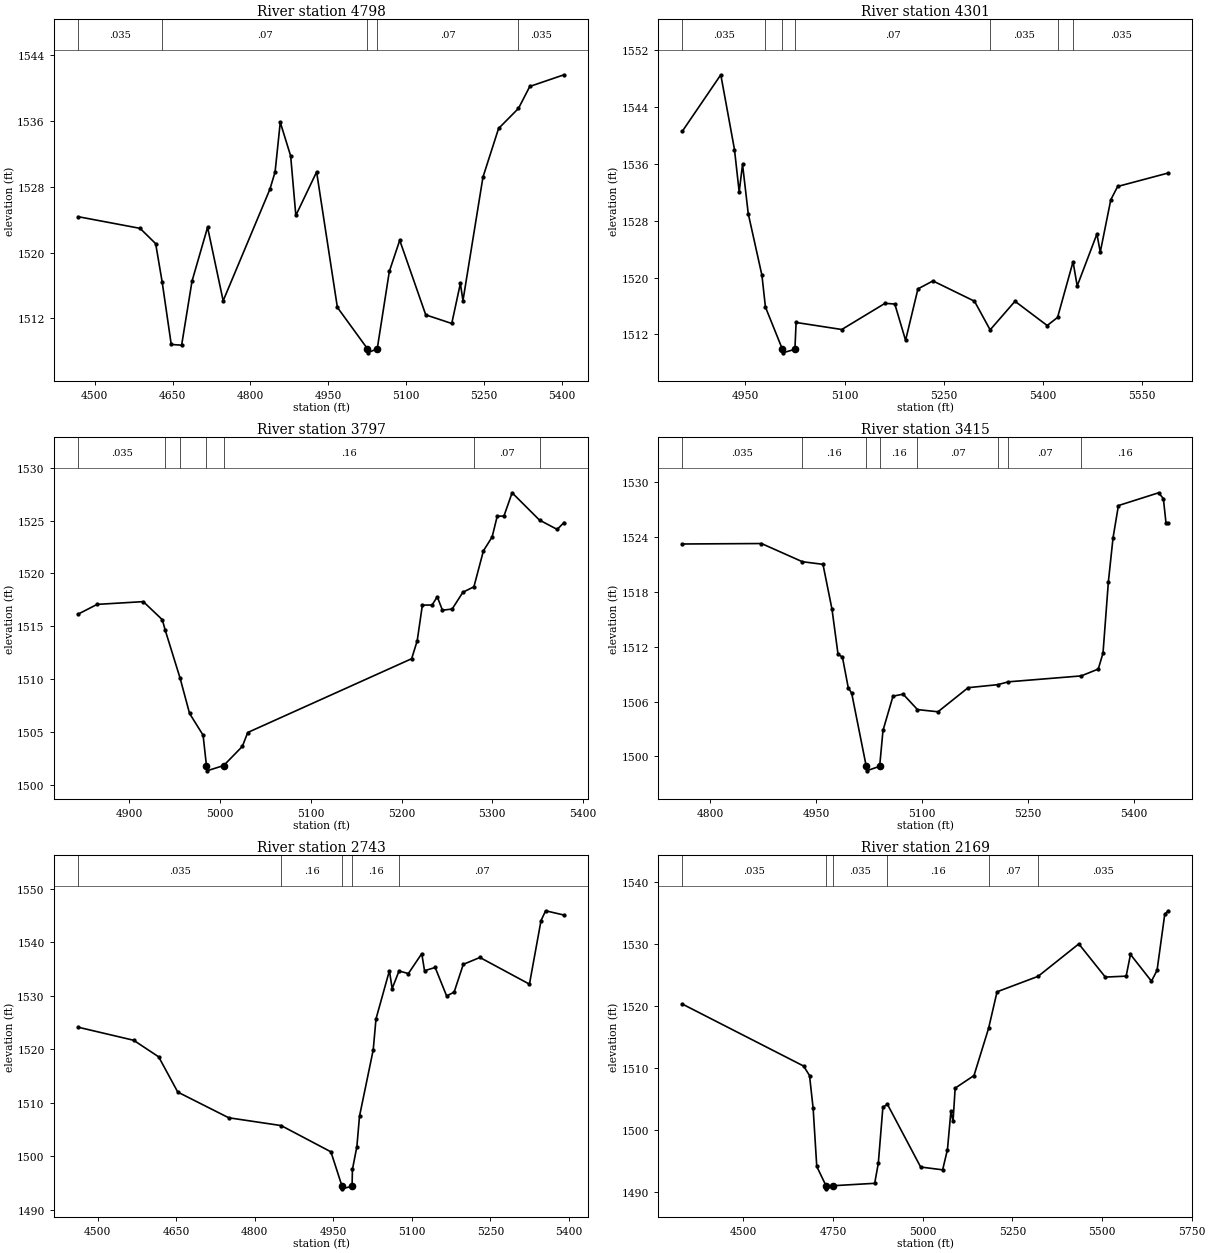
Type RM Length L Ch R = 1,4798,497,497,497
BEGIN DESCRIPTION:
Mapping XS 92bddb44
END DESCRIPTION:
XS GIS Cut Line= 3
      1625519.48      6980317.24      1625512.54      6979791.22
      1625488.27      6979382.20
#Sta/Elev= 30
  4468.2 1524.37  4587.5 1522.95  4617.5 1521.09  4630.0 1516.44  4647.5 1508.83
  4667.5 1508.74  4687.5 1516.52  4717.5 1523.08  4747.5 1514.14  4837.5 1527.70
  4847.5 1529.80  4857.5 1535.85  4877.5 1531.76  4887.5 1524.52  4927.5 1529.81
  4967.5 1513.34  5025.4 1508.31  5025.9 1507.81  5044.3 1508.31  5067.6 1517.72
  5087.6 1521.50  5137.7 1512.43  5187.8 1511.38  5204.4 1516.25  5209.4 1514.16
  5247.9 1529.18  5278.0 1535.10  5316.3 1537.54  5338.1 1540.21  5404.0 1541.63
#Mann=5,-1,0
  4468.2   0.035       0  4630.0    0.07       0  5025.4    0.07       0
  5044.3    0.07       0  5316.3   0.035       0
Bank Sta=5025.4,5044.3
Exp/Cntr=0.3,0.1

Type RM Length L Ch R = 1,4301,504,504,504
BEGIN DESCRIPTION:
Mapping XS c65f8133
END DESCRIPTION:
XS GIS Cut Line= 3
      1625942.76      6980124.25      1625904.55      6979981.85
      1625753.51      6979414.13
#Sta/Elev= 30
  4854.5 1540.56  4912.7 1548.50  4933.4 1537.99  4940.5 1532.03  4945.6 1535.90
  4954.2 1528.98  4974.9 1520.32  4980.2 1515.85  5005.9 1509.91  5006.4 1509.41
  5024.8 1509.91  5026.6 1513.68  5095.7 1512.69  5161.1 1516.37  5175.9 1516.27
  5192.2 1511.17  5210.9 1518.40  5233.6 1519.52  5296.4 1516.67  5320.1 1512.64
  5357.7 1516.66  5406.4 1513.25  5422.1 1514.39  5445.5 1522.21  5451.8 1518.81
  5481.6 1526.11  5486.7 1523.58  5502.6 1530.93  5513.0 1532.80  5589.4 1534.69
#Mann=7,-1,0
  4854.5   0.035       0  4980.2    0.07       0  5005.9    0.07       0
  5024.8    0.07       0  5320.1   0.035       0  5422.1    0.07       0
  5445.5   0.035       0
Bank Sta=5005.9,5024.8
Exp/Cntr=0.3,0.1

Type RM Length L Ch R = 1,3797,382,382,382
BEGIN DESCRIPTION:
Mapping XS 63f1eeaf
END DESCRIPTION:
XS GIS Cut Line= 3
      1626438.79      6979964.63      1626352.01      6979836.19
      1626174.94      6979499.41
#Sta/Elev= 30
  4843.6 1516.16  4864.5 1517.08  4915.4 1517.34  4936.4 1515.63  4939.4 1514.69
  4956.0 1510.10  4966.4 1506.78  4981.3 1504.73  4985.0 1501.86  4985.5 1501.36
  5004.0 1501.86  5024.6 1503.67  5030.5 1504.98  5211.2 1511.95  5217.3 1513.64
  5223.0 1517.01  5233.7 1517.02  5239.4 1517.80  5245.1 1516.53  5255.8 1516.64
  5267.7 1518.23  5279.8 1518.74  5290.3 1522.14  5299.9 1523.45  5305.5 1525.41
  5312.9 1525.42  5321.9 1527.62  5352.1 1525.04  5371.6 1524.16  5379.1 1524.81
#Mann=7,-1,0
  4843.6   0.035       0  4939.4    0.07       0  4956.0    0.16       0
  4985.0    0.07       0  5004.0    0.16       0  5279.8    0.07       0
  5352.1   0.035       0
Bank Sta=4985,5004
Exp/Cntr=0.3,0.1

Type RM Length L Ch R = 1,3415,672,672,672
BEGIN DESCRIPTION:
Mapping XS efc27fbc
END DESCRIPTION:
XS GIS Cut Line= 3
      1626845.05      6979775.42      1626652.35      6979633.07
      1626315.55      6979337.93
#Sta/Elev= 30
  4760.7 1523.26  4872.7 1523.31  4930.5 1521.32  4959.7 1521.03  4972.5 1516.10
  4981.0 1511.18  4987.2 1510.88  4995.5 1507.50  5000.3 1506.92  5020.9 1498.91
  5021.4 1498.41  5039.9 1498.91  5044.6 1502.83  5058.8 1506.59  5073.1 1506.81
  5093.4 1505.12  5122.4 1504.88  5165.1 1507.52  5207.0 1507.85  5221.9 1508.16
  5325.1 1508.81  5349.2 1509.56  5355.9 1511.31  5363.5 1519.12  5370.1 1523.94
  5377.7 1527.47  5434.6 1528.87  5441.3 1528.23  5445.1 1525.51  5448.1 1525.51
#Mann=8,-1,0
  4760.7   0.035       0  4930.5    0.16       0  5020.9    0.07       0
  5039.9    0.16       0  5093.4    0.07       0  5207.0   0.035       0
  5221.9    0.07       0  5325.1    0.16       0
Bank Sta=5020.9,5039.9
Exp/Cntr=0.3,0.1

Type RM Length L Ch R = 1,2743,574,574,574
BEGIN DESCRIPTION:
Mapping XS 7720c1c3
END DESCRIPTION:
XS GIS Cut Line= 3
      1626874.23      6979517.63      1626749.23      6978993.31
      1626619.49      6978626.59
#Sta/Elev= 30
  4462.7 1524.10  4568.7 1521.66  4616.5 1518.56  4653.0 1511.97  4750.2 1507.17
  4850.4 1505.71  4945.5 1500.80  4966.7 1494.38  4967.2 1493.88  4985.9 1494.38
  4986.6 1497.52  4995.1 1501.78  5000.1 1507.46  5026.3 1519.86  5031.6 1525.65
  5057.2 1534.66  5062.5 1531.33  5075.6 1534.62  5093.4 1534.13  5119.0 1537.86
  5124.3 1534.66  5144.6 1535.27  5166.5 1529.95  5180.8 1530.65  5198.3 1535.85
  5230.1 1537.14  5324.7 1532.15  5346.8 1544.03  5355.6 1545.87  5390.7 1545.07
#Mann=5,-1,0
  4462.7   0.035       0  4850.4    0.16       0  4966.7    0.07       0
  4985.9    0.16       0  5075.6    0.07       0
Bank Sta=4966.7,4985.9
Exp/Cntr=0.3,0.1

Type RM Length L Ch R = 1,2169,385,385,385
BEGIN DESCRIPTION:
Mapping XS 3a64a577
END DESCRIPTION:
XS GIS Cut Line= 3
      1627174.03      6979749.35      1627264.95      6979088.85
      1626913.63      6978497.23
#Sta/Elev= 30
  4329.7 1520.29  4668.0 1510.31  4684.4 1508.78  4694.5 1503.49  4704.6 1494.15
  4730.4 1491.05  4730.9 1490.55  4749.6 1491.05  4866.1 1491.44  4876.2 1494.66
  4889.0 1503.71  4901.7 1504.15  4994.3 1494.06  5055.6 1493.61  5069.0 1496.87
  5078.7 1503.06  5084.6 1501.39  5090.5 1506.76  5143.0 1508.78  5183.7 1516.38
  5207.3 1522.26  5321.8 1524.75  5435.3 1529.97  5509.2 1524.63  5567.3 1524.78
  5579.4 1528.27  5637.9 1523.97  5653.5 1525.72  5674.9 1534.72  5684.5 1535.30
#Mann=6,-1,0
  4329.7   0.035       0  4730.4    0.07       0  4749.6   0.035       0
  4901.7    0.16       0  5183.7    0.07       0  5321.8   0.035       0
Bank Sta=4730.4,4749.6
Exp/Cntr=0.3,0.1

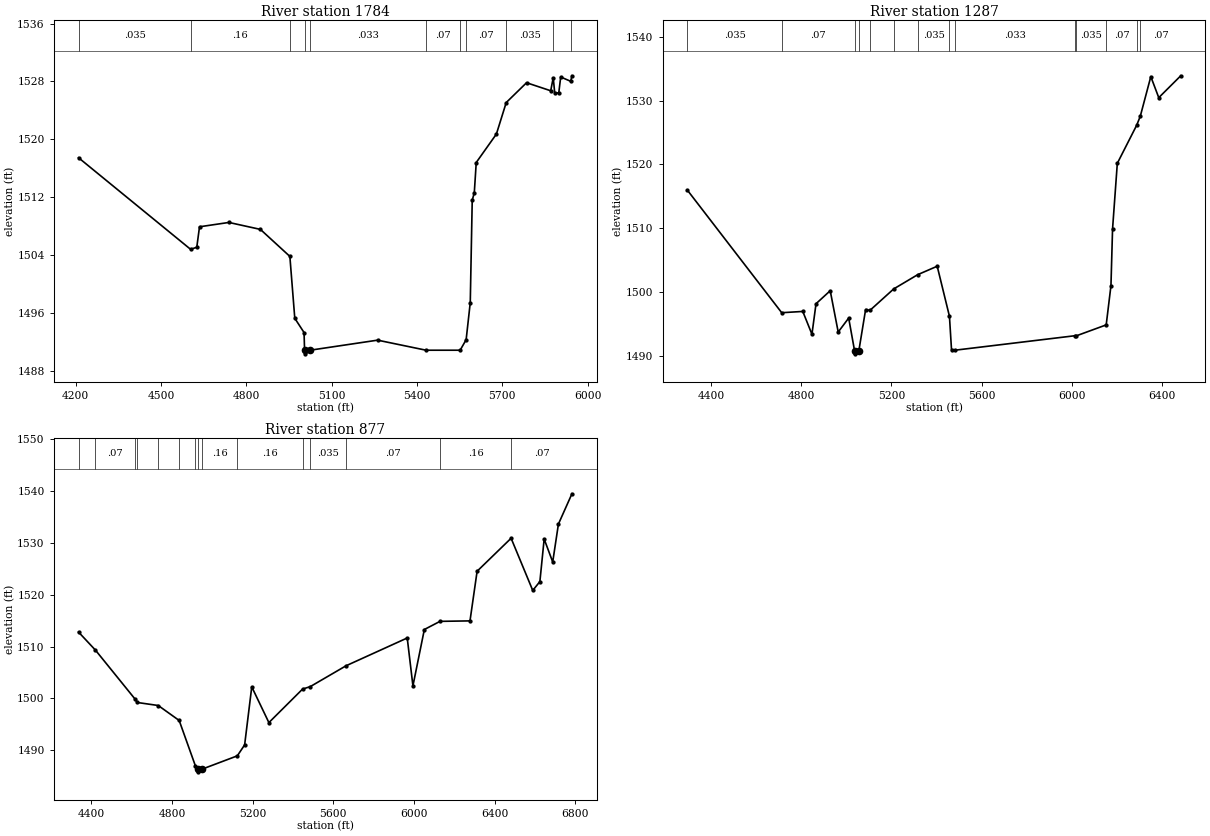
Type RM Length L Ch R = 1,1784,497,497,497
BEGIN DESCRIPTION:
Mapping XS e052390f
END DESCRIPTION:
XS GIS Cut Line= 4
      1627336.79      6979768.91      1627551.63      6979393.47
      1627594.52      6979038.93      1626949.16      6978348.34
#Sta/Elev= 30
  4210.3 1517.46  4604.3 1504.81  4626.1 1505.09  4635.7 1507.92  4739.0 1508.52
  4849.8 1507.56  4953.4 1503.83  4970.7 1495.28  5003.3 1493.31  5005.1 1490.87
  5005.6 1490.37  5024.3 1490.87  5261.9 1492.26  5432.4 1490.87  5552.1 1490.87
  5573.2 1492.32  5587.7 1497.45  5594.6 1511.58  5601.9 1512.63  5608.7 1516.80
  5679.6 1520.73  5714.1 1525.08  5785.6 1527.82  5870.6 1526.71  5879.4 1528.51
  5884.7 1526.40  5898.9 1526.42  5905.7 1528.61  5940.8 1528.02  5945.2 1528.78
#Mann=11,-1,0
  4210.3   0.035       0  4604.3    0.16       0  4953.4   0.033       0
  5005.1   0.033       0  5024.3   0.033       0  5432.4    0.07       0
  5552.1   0.035       0  5573.2    0.07       0  5714.1   0.035       0
  5879.4    0.07       0  5940.8   0.035       0
Bank Sta=5005.1,5024.3
Exp/Cntr=0.3,0.1

Type RM Length L Ch R = 1,1287,410,410,410
BEGIN DESCRIPTION:
Mapping XS 97fd47b7
END DESCRIPTION:
XS GIS Cut Line= 5
      1627731.77      6980020.60      1627907.54      6979343.56
      1627794.69      6979044.08      1627369.34      6978603.54
      1626972.23      6978212.94
#Sta/Elev= 30
  4294.7 1515.97  4713.4 1496.74  4806.9 1496.94  4847.5 1493.36  4865.6 1498.15
  4928.6 1500.19  4964.0 1493.71  5010.5 1495.90  5036.5 1490.79  5037.0 1490.29
  5055.7 1490.79  5085.6 1497.24  5104.6 1497.10  5210.2 1500.47  5316.4 1502.70
  5403.2 1504.03  5457.5 1496.18  5466.8 1490.87  5484.2 1490.87  6016.6 1493.14
  6017.7 1493.08  6152.9 1494.83  6174.0 1500.98  6181.1 1509.88  6202.2 1520.17
  6288.1 1526.14  6304.1 1527.55  6350.8 1533.77  6386.1 1530.47  6483.6 1533.90
#Mann=14,-1,0
  4294.7   0.035       0  4713.4    0.07       0  5036.5    0.07       0
  5055.7    0.07       0  5104.6    0.16       0  5210.2    0.07       0
  5316.4   0.035       0  5457.5    0.07       0  5484.2   0.033       0
  6016.6    0.16       0  6017.7   0.035       0  6152.9    0.07       0
  6288.1   0.035       0  6304.1    0.07       0
Bank Sta=5036.5,5055.7
Exp/Cntr=0.3,0.1

Type RM Length L Ch R = 1,877,0,0,0
BEGIN DESCRIPTION:
Mapping XS 441a7542
END DESCRIPTION:
XS GIS Cut Line= 3
      1628061.62      6980009.79      1628299.03      6979390.33
      1627038.64      6978129.61
#Sta/Elev= 30
  4336.6 1512.79  4420.7 1509.30  4617.4 1499.86  4628.1 1499.23  4731.8 1498.65
  4835.6 1495.77  4915.9 1487.04  4928.6 1486.38  4929.1 1485.88  4947.9 1486.38
  5123.8 1488.96  5160.1 1491.07  5195.4 1502.24  5280.3 1495.36  5447.3 1501.81
  5485.6 1502.29  5662.9 1506.30  5966.2 1511.65  5994.4 1502.43  6051.0 1513.28
  6128.7 1514.85  6277.3 1514.94  6312.6 1524.50  6481.1 1530.85  6588.4 1520.80
  6623.8 1522.51  6645.0 1530.70  6687.4 1526.28  6715.7 1533.58  6782.7 1539.41
#Mann=15,-1,0
  4336.6   0.035       0  4420.7    0.07       0  4617.4   0.035       0
  4628.1    0.07       0  4731.8    0.16       0  4835.6    0.07       0
  4915.9    0.16       0  4928.6    0.07       0  4947.9    0.16       0
  5123.8    0.16       0  5447.3    0.07       0  5485.6   0.035       0
  5662.9    0.07       0  6128.7    0.16       0  6481.1    0.07       0
Bank Sta=4928.6,4947.9
Exp/Cntr=0.3,0.1

Chan Stop Cuts=-1