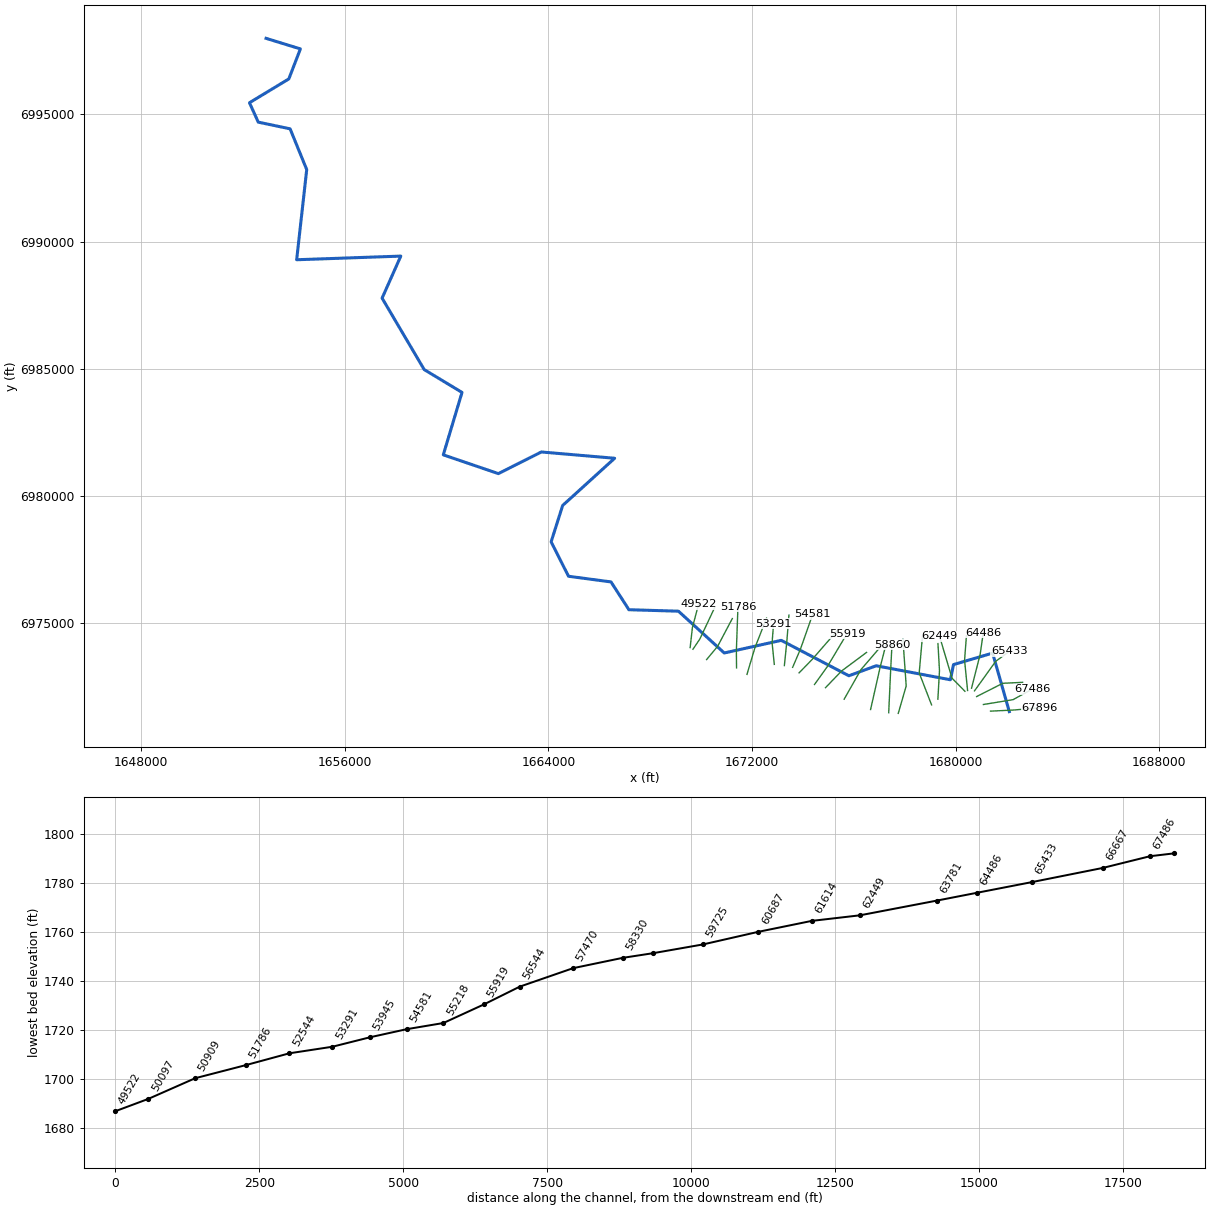
--- Swager Creek.prj (project) ---

Proj Title=Swager Creek Base Level Engineering
Current Plan=p01
Default Exp/Contr=0.3,0.1
English Units
Geom File=g01
Flow File=f01
Plan File=p01
BEGIN DESCRIPTION:
Swager Creek
END DESCRIPTION:

--- Swager Creek.p01 (plan) ---

Plan Title=Multiple Run
Short Identifier=Multiple
Geom File=g01
Flow File=f01
Subcritical Flow
K Sum by GR= 0
Std Step Tol= 0.01
Critical Tol= 0.01
Num of Std Step Trials= 20
Max Error Tol= 0.3
Flow Tol Ratio= 0.001
Split Flow NTrial= 30
Split Flow Tol= 0.02
Split Flow Ratio= 0.02
Log Output Level= 0
Friction Slope Method= 1
Unsteady Friction Slope Method= 2
Unsteady Bridges Friction Slope Method= 1
Parabolic Critical Depth
Global Vel Dist=  1 , 1 , 1
Global Log Level= 0
CheckData=True
Encroach Param= -1, 0, 0, 0
BEGIN DESCRIPTION:
Multiple Run
END DESCRIPTION:

--- Swager Creek.f01 (steady flow) ---

Flow Title=Multiple
Number of Profiles=7
Profile Names=10-year,25-year,50-year,1pct_min,100-year,1pct_plu,500-year
River Rch & RM= Swager Creek,Reach-1,67896
     262     361     441     269     537    1072     804
River Rch & RM= Swager Creek,Reach-1,64486
     349     486     600     369     736    1468    1119
River Rch & RM= Swager Creek,Reach-1,61614
     456     644     801     496     989    1973    1525
River Rch & RM= Swager Creek,Reach-1,53291
     488     691     862     534    1066    2128    1653
River Rch & RM= Swager Creek,Reach-1,51786
     534     762     955     595    1187    2368    1856
River Rch & RM= Swager Creek,Reach-1,47310
    1150    1699    2180    1386    2766    5519    4516
River Rch & RM= Swager Creek,Reach-1,35274
    1436    2136    2755    1760    3512    7008    5787
River Rch & RM= Swager Creek,Reach-1,28698
    1501    2236    2887    1846    3683    7349    6079
River Rch & RM= Swager Creek,Reach-1,25076
    1572    2344    3027    1937    3864    7710    6381
River Rch & RM= Swager Creek,Reach-1,17460
    1800    2698    3499    2247    4483    8944    7456
River Rch & RM= Swager Creek,Reach-1,6577
    1831    2746    3561    2286    4562    9103    7589
River Rch & RM= Swager Creek,Reach-1,1434
    2171    3275    4265    2749    5484   10943    9192
Boundary for River Rch & Prof#=Swager Creek,Reach-1,1
Up Type=0
Dn Type=3
Dn Slope=0.005
Boundary for River Rch & Prof#=Swager Creek,Reach-1,2
Up Type=0
Dn Type=3
Dn Slope=0.005
Boundary for River Rch & Prof#=Swager Creek,Reach-1,3
Up Type=0
Dn Type=3
Dn Slope=0.005
Boundary for River Rch & Prof#=Swager Creek,Reach-1,4
Up Type=0
Dn Type=3
Dn Slope=0.005
Boundary for River Rch & Prof#=Swager Creek,Reach-1,5
Up Type=0
Dn Type=3
Dn Slope=0.005
Boundary for River Rch & Prof#=Swager Creek,Reach-1,6
Up Type=0
Dn Type=3
Dn Slope=0.005
Boundary for River Rch & Prof#=Swager Creek,Reach-1,7
Up Type=0
Dn Type=3
Dn Slope=0.005

--- Swager Creek.g01 (geometry) ---

Geom Title=Existing Conditions

River Reach=Swager Creek,Reach-1
Reach XY= 30
      1682105.00      6971538.00      1681449.93      6973835.93
      1679912.95      6973385.19      1679791.03      6972788.55
      1676875.36      6973338.36      1675801.77      6972945.83
      1673145.34      6974336.63      1670906.50      6973841.46
      1669107.43      6975482.48      1667160.94      6975540.26
      1666457.58      6976632.28      1664788.32      6976854.64
      1664105.07      6978208.03      1664558.55      6979636.53
      1666599.95      6981490.55      1663720.22      6981737.48
      1662032.15      6980887.71      1659868.40      6981624.70
      1660603.92      6984077.45      1659118.36      6984974.65
      1657464.11      6987781.27      1658199.49      6989432.73
      1654108.54      6989289.46      1654502.94      6992832.14
      1653849.89      6994432.89      1652598.83      6994695.86
      1652254.64      6995458.15      1653799.82      6996393.44
      1654254.88      6997572.95      1652905.00      6997988.00

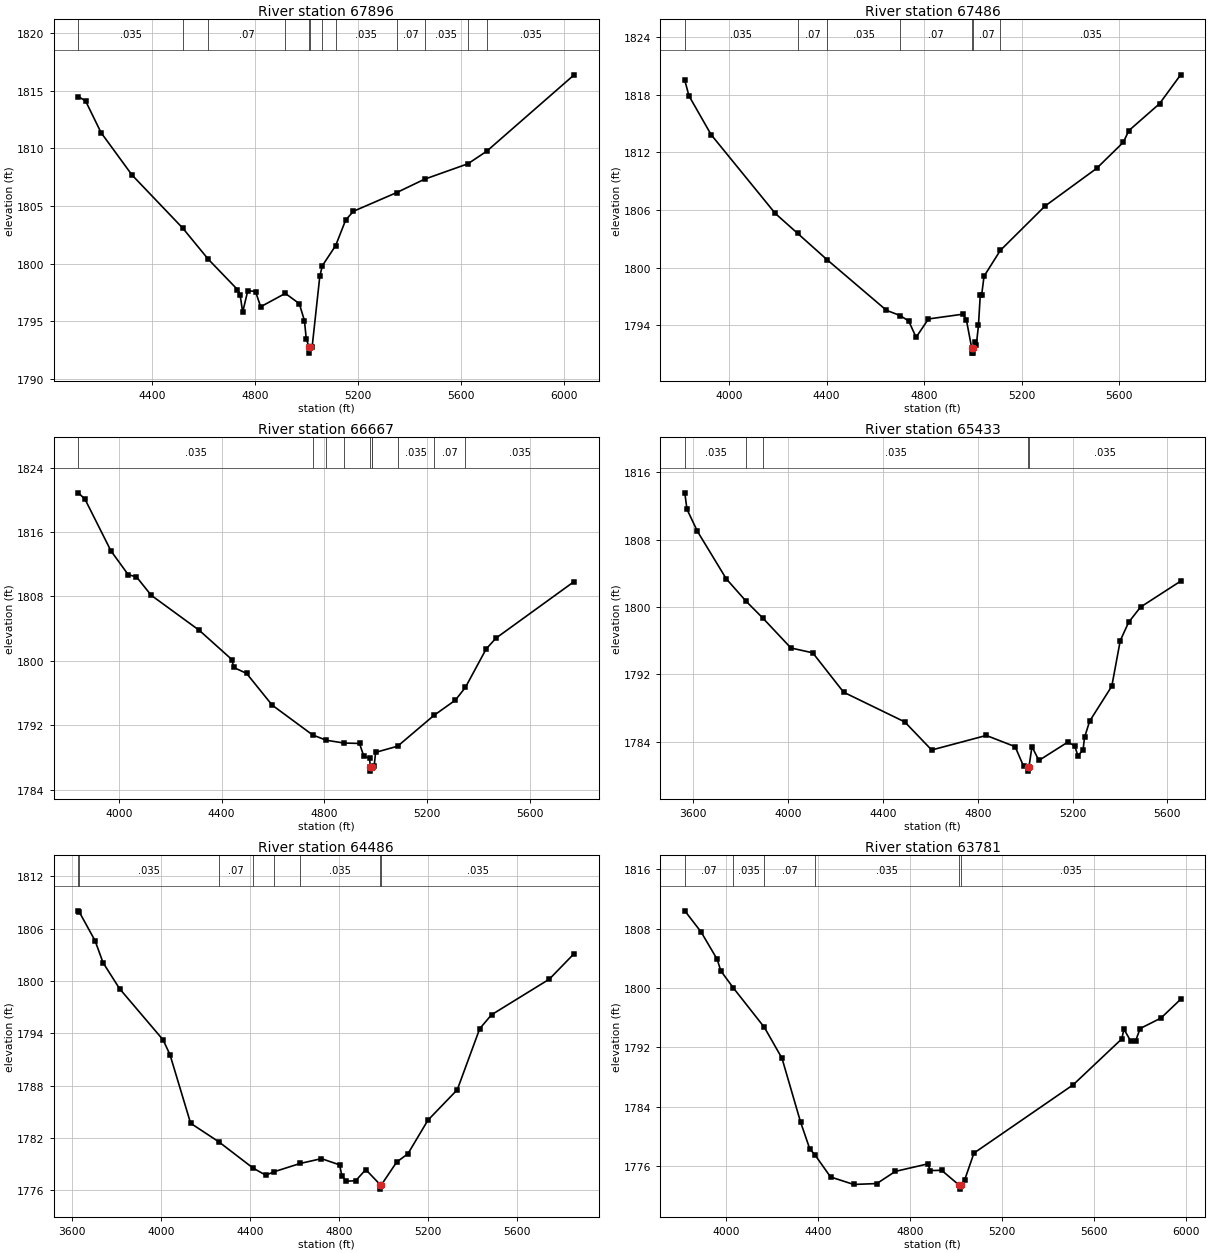
Type RM Length L Ch R = 1,67896,410,410,410
BEGIN DESCRIPTION:
Swager Creek 117.0
END DESCRIPTION:
XS GIS Cut Line= 3
      1681366.77      6971555.88      1682253.95      6971598.42
      1683290.20      6971684.33
#Sta/Elev= 30
  4111.8 1814.49  4140.1 1814.10  4200.1 1811.36  4320.3 1807.69  4518.1 1803.07
  4617.1 1800.38  4730.7 1797.75  4740.7 1797.32  4750.8 1795.79  4770.8 1797.66
  4800.8 1797.58  4820.8 1796.26  4916.7 1797.42  4971.0 1796.53  4991.0 1795.06
  4998.0 1793.50  5009.0 1792.74  5009.3 1792.24  5013.2 1792.74  5021.1 1792.81
  5050.8 1798.91  5060.7 1799.82  5112.3 1801.56  5151.6 1803.79  5181.7 1804.54
  5349.7 1806.16  5458.0 1807.32  5626.9 1808.66  5700.0 1809.75  6039.8 1816.37
#Mann=12,-1,0
  4111.8   0.035       0  4518.1    0.16       0  4617.1    0.07       0
  4916.7   0.035       0  5009.0   0.035       0  5013.2   0.035       0
  5060.7    0.07       0  5112.3   0.035       0  5349.7    0.07       0
  5458.0   0.035       0  5626.9    0.07       0  5700.0   0.035       0
Bank Sta=5009,5013.2
Exp/Cntr=0.3,0.1

Type RM Length L Ch R = 1,67486,819,819,819
BEGIN DESCRIPTION:
Mapping XS cf5b50e2
END DESCRIPTION:
XS GIS Cut Line= 3
      1681088.34      6971816.64      1682255.01      6972007.62
      1683000.79      6972420.40
#Sta/Elev= 30
  3817.8 1819.52  3834.7 1817.91  3925.9 1813.85  4189.3 1805.64  4280.7 1803.57
  4401.4 1800.83  4645.3 1795.55  4701.1 1795.01  4736.5 1794.44  4766.9 1792.74
  4817.6 1794.65  4959.5 1795.15  4973.0 1794.59  4995.4 1791.59  4995.7 1791.09
  4999.3 1791.09  4999.6 1791.59  5008.4 1792.29  5014.1 1791.95  5022.8 1793.97
  5030.2 1797.12  5035.9 1797.14  5045.7 1799.10  5112.4 1801.79  5295.8 1806.41
  5507.7 1810.34  5617.2 1813.06  5640.0 1814.28  5765.8 1817.08  5852.4 1820.09
#Mann=7,-1,0
  3817.8   0.035       0  4280.7    0.07       0  4401.4   0.035       0
  4701.1    0.07       0  4995.4    0.07       0  4999.6    0.07       0
  5112.4   0.035       0
Bank Sta=4995.4,4999.6
Exp/Cntr=0.3,0.1

Type RM Length L Ch R = 1,66667,1234,1234,1234
BEGIN DESCRIPTION:
Mapping XS 35b3bb63
END DESCRIPTION:
XS GIS Cut Line= 3
      1680821.71      6972128.82      1681849.45      6972649.63
      1682627.24      6972687.82
#Sta/Elev= 30
  3841.9 1820.87  3867.8 1820.08  3968.9 1813.66  4036.2 1810.70  4068.3 1810.43
  4125.9 1808.14  4313.3 1803.78  4439.8 1800.16  4446.9 1799.18  4497.1 1798.44
  4596.7 1794.50  4754.1 1790.80  4807.1 1790.14  4876.2 1789.79  4936.9 1789.74
  4953.6 1788.15  4975.8 1787.91  4979.3 1786.80  4979.6 1786.30  4983.6 1786.80
  4985.7 1786.87  4994.1 1786.98  4999.6 1788.63  5085.5 1789.40  5227.0 1793.23
  5310.0 1795.11  5349.5 1796.71  5430.1 1801.47  5467.9 1802.81  5772.8 1809.85
#Mann=10,-1,0
  3841.9   0.035       0  4754.1    0.16       0  4807.1    0.07       0
  4876.2   0.035       0  4979.3    0.07       0  4983.6   0.035       0
  4985.7    0.07       0  5085.5   0.035       0  5227.0    0.07       0
  5349.5   0.035       0
Bank Sta=4979.3,4983.6
Exp/Cntr=0.3,0.1

Type RM Length L Ch R = 1,65433,947,947,947
BEGIN DESCRIPTION:
Mapping XS 3ded24b0
END DESCRIPTION:
XS GIS Cut Line= 3
      1680737.67      6972351.40      1681570.98      6973514.56
      1682105.43      6973903.25
#Sta/Elev= 30
  3564.1 1813.56  3573.2 1811.61  3617.4 1808.98  3739.0 1803.34  3822.8 1800.67
  3894.4 1798.64  4011.7 1795.12  4103.9 1794.54  4234.1 1789.86  4492.0 1786.33
  4605.5 1782.99  4835.9 1784.72  4957.5 1783.39  4993.2 1781.07  5011.7 1780.98
  5012.0 1780.48  5016.1 1780.98  5028.6 1783.39  5057.9 1781.75  5179.3 1783.92
  5208.6 1783.51  5222.5 1782.31  5244.2 1783.00  5250.4 1784.48  5272.0 1786.42
  5365.5 1790.58  5401.1 1795.99  5436.6 1798.18  5486.8 1799.98  5655.8 1803.06
#Mann=5,-1,0
  3564.1   0.035       0  3822.8    0.07       0  3894.4   0.035       0
  5011.7   0.035       0  5016.1   0.035       0
Bank Sta=5011.7,5016.1
Exp/Cntr=0.3,0.1

Type RM Length L Ch R = 1,64486,705,705,705
BEGIN DESCRIPTION:
Mapping XS cc5e915e
END DESCRIPTION:
XS GIS Cut Line= 3
      1680621.79      6972458.10      1680962.07      6973798.36
      1681083.59      6974638.64
#Sta/Elev= 30
  3627.4 1808.03  3632.5 1807.86  3703.0 1804.59  3738.8 1802.08  3813.0 1799.11
  4009.0 1793.24  4040.0 1791.54  4132.8 1783.69  4260.3 1781.55  4414.0 1778.55
  4470.8 1777.74  4509.8 1778.14  4625.7 1779.08  4721.7 1779.63  4803.6 1778.92
  4813.8 1777.65  4834.2 1777.06  4875.2 1777.09  4921.3 1778.38  4986.5 1776.64
  4986.9 1776.14  4991.8 1776.64  5060.3 1779.24  5110.9 1780.19  5201.0 1784.04
  5333.1 1787.53  5434.2 1794.53  5487.3 1796.12  5747.4 1800.20  5859.2 1803.13
#Mann=8,-1,0
  3627.4    0.07       0  3632.5   0.035       0  4260.3    0.07       0
  4414.0   0.035       0  4509.8    0.07       0  4625.7   0.035       0
  4986.5   0.035       0  4991.8   0.035       0
Bank Sta=4986.5,4991.8
Exp/Cntr=0.3,0.1

Type RM Length L Ch R = 1,63781,1332,1332,1332
BEGIN DESCRIPTION:
Mapping XS 7347ef94
END DESCRIPTION:
XS GIS Cut Line= 3
      1680465.54      6972367.80      1680347.48      6973551.83
      1680420.38      6974513.37
#Sta/Elev= 30
  3821.8 1810.42  3892.4 1807.58  3962.7 1803.87  3978.1 1802.33  4032.9 1800.02
  4167.7 1794.70  4244.1 1790.54  4324.5 1781.97  4364.7 1778.33  4387.9 1777.49
  4455.1 1774.54  4555.6 1773.53  4656.1 1773.65  4736.5 1775.29  4877.2 1776.30
  4888.9 1775.40  4937.5 1775.44  5015.2 1773.40  5015.6 1772.90  5020.5 1773.40
  5037.9 1774.16  5078.1 1777.76  5509.3 1786.97  5719.9 1793.14  5729.9 1794.45
  5760.0 1792.82  5780.1 1792.86  5800.1 1794.55  5890.4 1795.96  5976.0 1798.49
#Mann=6,-1,0
  3821.8    0.07       0  4032.9   0.035       0  4167.7    0.07       0
  4387.9   0.035       0  5015.2   0.035       0  5020.5   0.035       0
Bank Sta=5015.2,5020.5
Exp/Cntr=0.3,0.1

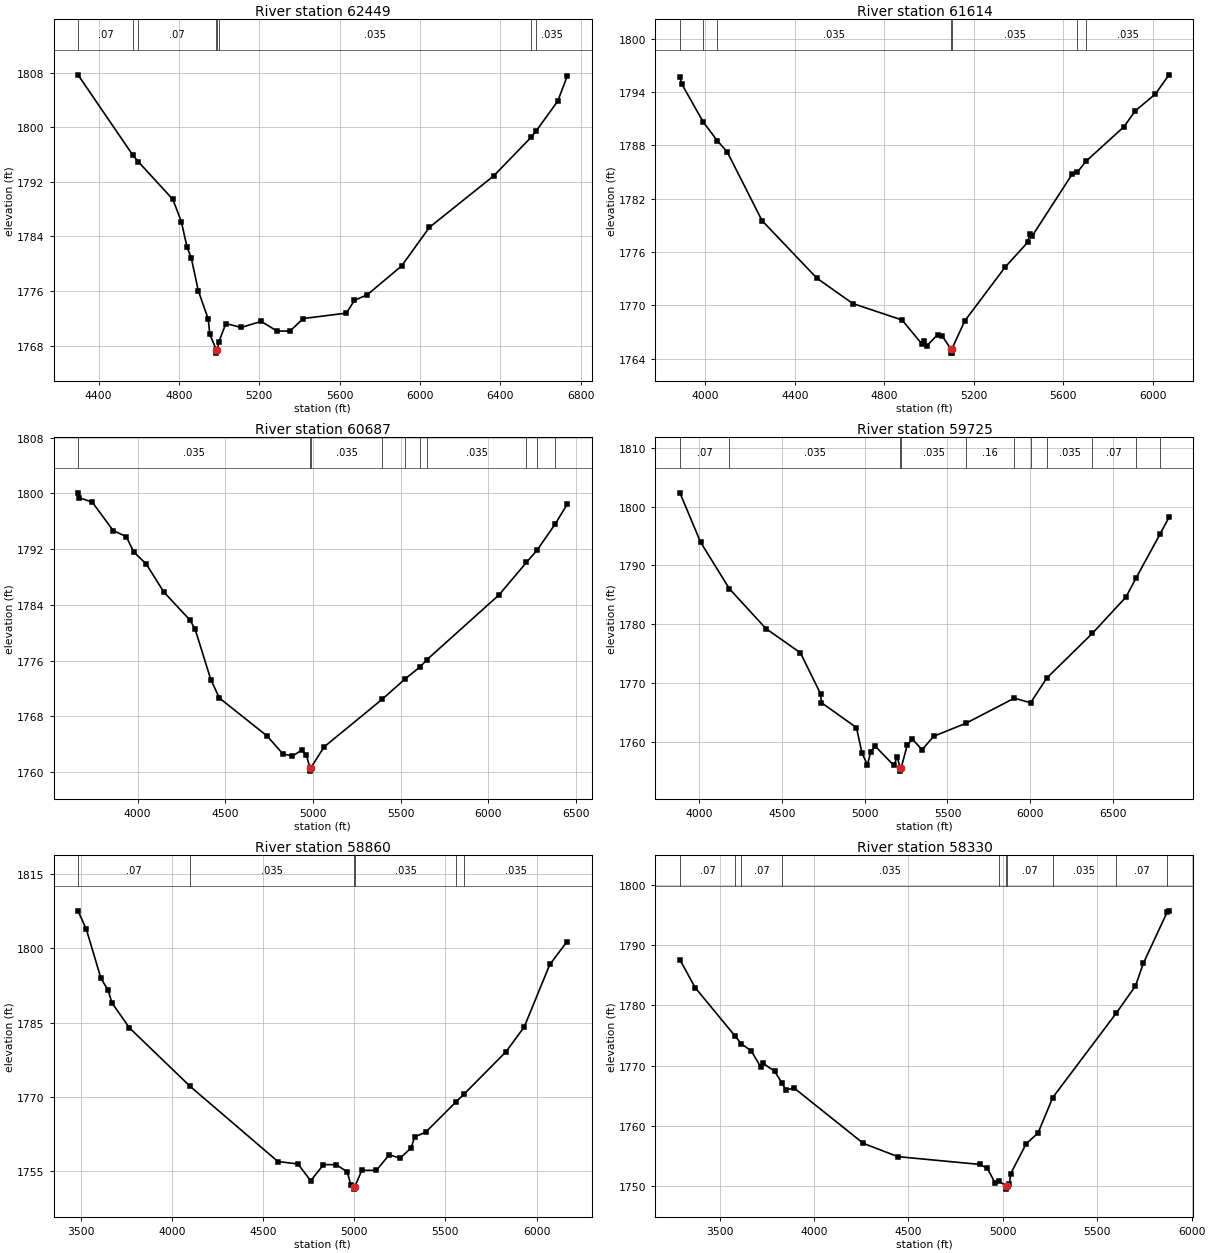
Type RM Length L Ch R = 1,62449,835,835,835
BEGIN DESCRIPTION:
Mapping XS cc383341
END DESCRIPTION:
XS GIS Cut Line= 3
      1680361.35      6972336.57      1679854.43      6972850.44
      1679364.85      6974492.79
#Sta/Elev= 30
  4297.1 1807.66  4570.0 1795.90  4597.4 1794.93  4769.3 1789.42  4811.7 1786.15
  4840.0 1782.44  4861.2 1780.83  4896.6 1775.99  4946.0 1771.86  4953.2 1769.69
  4985.7 1767.39  4986.2 1766.89  4991.2 1767.39  4998.6 1768.53  5033.2 1771.22
  5110.3 1770.65  5209.4 1771.54  5287.7 1770.13  5352.5 1770.11  5418.8 1771.96
  5633.4 1772.75  5673.8 1774.62  5738.1 1775.45  5909.1 1779.68  6046.9 1785.31
  6366.2 1792.83  6552.6 1798.48  6578.1 1799.41  6686.0 1803.80  6732.7 1807.42
#Mann=8,-1,0
  4297.1    0.07       0  4570.0   0.035       0  4597.4    0.07       0
  4985.7   0.035       0  4991.2    0.07       0  4998.6   0.035       0
  6552.6    0.07       0  6578.1   0.035       0
Bank Sta=4985.7,4991.2
Exp/Cntr=0.3,0.1

Type RM Length L Ch R = 1,61614,927,927,927
BEGIN DESCRIPTION:
Mapping XS d346481d
END DESCRIPTION:
XS GIS Cut Line= 3
      1679299.51      6972026.76      1679362.01      6973143.96
      1679302.11      6974209.03
#Sta/Elev= 30
  3887.0 1795.72  3894.5 1794.96  3991.1 1790.65  4054.5 1788.53  4098.6 1787.27
  4253.9 1779.54  4499.2 1773.05  4659.4 1770.20  4879.8 1768.34  4967.5 1765.67
  4979.9 1765.98  4990.0 1765.42  5038.4 1766.69  5060.1 1766.50  5097.2 1765.11
  5097.7 1764.61  5102.6 1764.61  5103.0 1765.11  5160.2 1768.25  5340.5 1774.30
  5440.7 1777.08  5450.7 1778.04  5460.7 1777.78  5641.0 1784.81  5662.2 1784.97
  5702.0 1786.23  5871.4 1790.11  5921.4 1791.89  6011.6 1793.79  6072.7 1795.96
#Mann=7,-1,0
  3887.0   0.035       0  3991.1    0.07       0  4054.5   0.035       0
  5097.2   0.035       0  5103.0   0.035       0  5662.2    0.07       0
  5702.0   0.035       0
Bank Sta=5097.2,5103
Exp/Cntr=0.3,0.1

Type RM Length L Ch R = 1,60687,962,962,962
BEGIN DESCRIPTION:
Mapping XS d8a52e3a
END DESCRIPTION:
XS GIS Cut Line= 3
      1679051.05      6971801.47      1678564.96      6973058.37
      1678693.30      6974494.42
#Sta/Elev= 30
  3660.4 1800.07  3668.0 1799.36  3741.8 1798.73  3861.6 1794.64  3935.3 1793.80
  3978.3 1791.58  4049.7 1789.86  4149.9 1785.83  4297.8 1781.85  4327.7 1780.56
  4417.9 1773.27  4466.7 1770.63  4739.4 1765.17  4829.2 1762.61  4883.7 1762.31
  4938.3 1763.17  4962.9 1762.42  4983.2 1760.64  4983.7 1760.14  4989.1 1760.64
  5063.8 1763.61  5395.6 1770.46  5527.1 1773.39  5611.7 1775.11  5651.2 1776.15
  6061.8 1785.43  6217.6 1790.08  6278.6 1791.84  6382.5 1795.62  6449.8 1798.40
#Mann=10,-1,0
  3660.4   0.035       0  4983.2   0.035       0  4989.1   0.035       0
  5395.6    0.07       0  5527.1   0.035       0  5611.7    0.07       0
  5651.2   0.035       0  6217.6    0.07       0  6278.6   0.035       0
  6382.5    0.07       0
Bank Sta=4983.2,4989.1
Exp/Cntr=0.3,0.1

Type RM Length L Ch R = 1,59725,865,865,865
BEGIN DESCRIPTION:
Mapping XS feb578b1
END DESCRIPTION:
XS GIS Cut Line= 3
      1677742.05      6971468.10      1678054.54      6972544.48
      1677926.07      6974377.86
#Sta/Elev= 30
  3881.5 1802.36  4006.3 1793.97  4180.8 1786.02  4402.0 1779.24  4610.3 1775.12
  4732.5 1768.14  4737.7 1766.63  4949.4 1762.38  4983.0 1758.06  5015.9 1756.01
  5035.9 1758.28  5064.1 1759.18  5176.3 1755.93  5196.3 1757.46  5213.3 1755.47
  5213.8 1754.97  5219.5 1755.47  5256.5 1759.37  5286.5 1760.44  5346.7 1758.62
  5416.9 1760.91  5611.0 1763.11  5904.8 1767.40  6002.7 1766.60  6100.6 1770.81
  6376.1 1778.42  6579.7 1784.61  6641.0 1787.85  6786.1 1795.34  6840.2 1798.20
#Mann=11,-1,0
  3881.5    0.07       0  4180.8   0.035       0  5213.3   0.035       0
  5219.5   0.035       0  5611.0    0.16       0  5904.8   0.035       0
  6002.7    0.07       0  6100.6   0.035       0  6376.1    0.07       0
  6641.0   0.035       0  6786.1    0.07       0
Bank Sta=5213.3,5219.5
Exp/Cntr=0.3,0.1

Type RM Length L Ch R = 1,58860,530,530,530
BEGIN DESCRIPTION:
Mapping XS d8d965c1
END DESCRIPTION:
XS GIS Cut Line= 3
      1677367.04      6971492.41      1677436.49      6973009.76
      1677495.51      6974172.92
#Sta/Elev= 30
  3484.2 1807.60  3529.8 1803.88  3609.9 1794.00  3650.0 1791.51  3670.0 1789.04
  3766.4 1783.96  4099.1 1772.16  4580.9 1756.97  4691.1 1756.47  4761.1 1753.08
  4831.2 1756.33  4901.3 1756.34  4961.3 1754.86  4981.4 1752.24  4996.6 1751.89
  4997.1 1751.39  5002.9 1751.89  5041.4 1755.18  5121.5 1755.19  5191.6 1758.32
  5251.7 1757.65  5311.8 1759.71  5331.8 1761.95  5391.9 1762.89  5559.1 1769.04
  5601.9 1770.56  5832.4 1779.13  5932.6 1784.15  6072.8 1796.76  6167.8 1801.40
#Mann=6,-1,0
  3484.2    0.07       0  4099.1   0.035       0  4996.6   0.035       0
  5002.9   0.035       0  5559.1    0.07       0  5601.9   0.035       0
Bank Sta=4996.6,5002.9
Exp/Cntr=0.3,0.1

Type RM Length L Ch R = 1,58330,860,860,860
BEGIN DESCRIPTION:
Mapping XS 91609e7f
END DESCRIPTION:
XS GIS Cut Line= 3
      1676655.24      6971619.15      1677033.71      6973296.22
      1677252.46      6974139.98
#Sta/Elev= 30
  3289.1 1787.61  3369.9 1782.97  3580.6 1774.95  3614.3 1773.64  3667.2 1772.45
  3716.5 1769.82  3728.7 1770.40  3790.2 1769.09  3830.8 1767.08  3851.2 1765.92
  3892.8 1766.31  4260.7 1757.08  4443.8 1754.87  4876.9 1753.58  4917.9 1752.93
  4958.9 1750.47  4977.0 1750.85  5017.2 1749.97  5017.7 1749.47  5023.9 1749.97
  5034.7 1750.38  5041.2 1752.03  5123.8 1757.03  5185.8 1758.77  5264.0 1764.69
  5599.2 1778.67  5702.3 1783.25  5743.7 1786.99  5870.4 1795.54  5880.0 1795.74
#Mann=10,-1,0
  3289.1    0.07       0  3580.6   0.035       0  3614.3    0.07       0
  3830.8   0.035       0  4977.0    0.07       0  5017.2    0.07       0
  5023.9    0.07       0  5264.0   0.035       0  5599.2    0.07       0
  5870.4   0.035       0
Bank Sta=5017.2,5023.9
Exp/Cntr=0.3,0.1

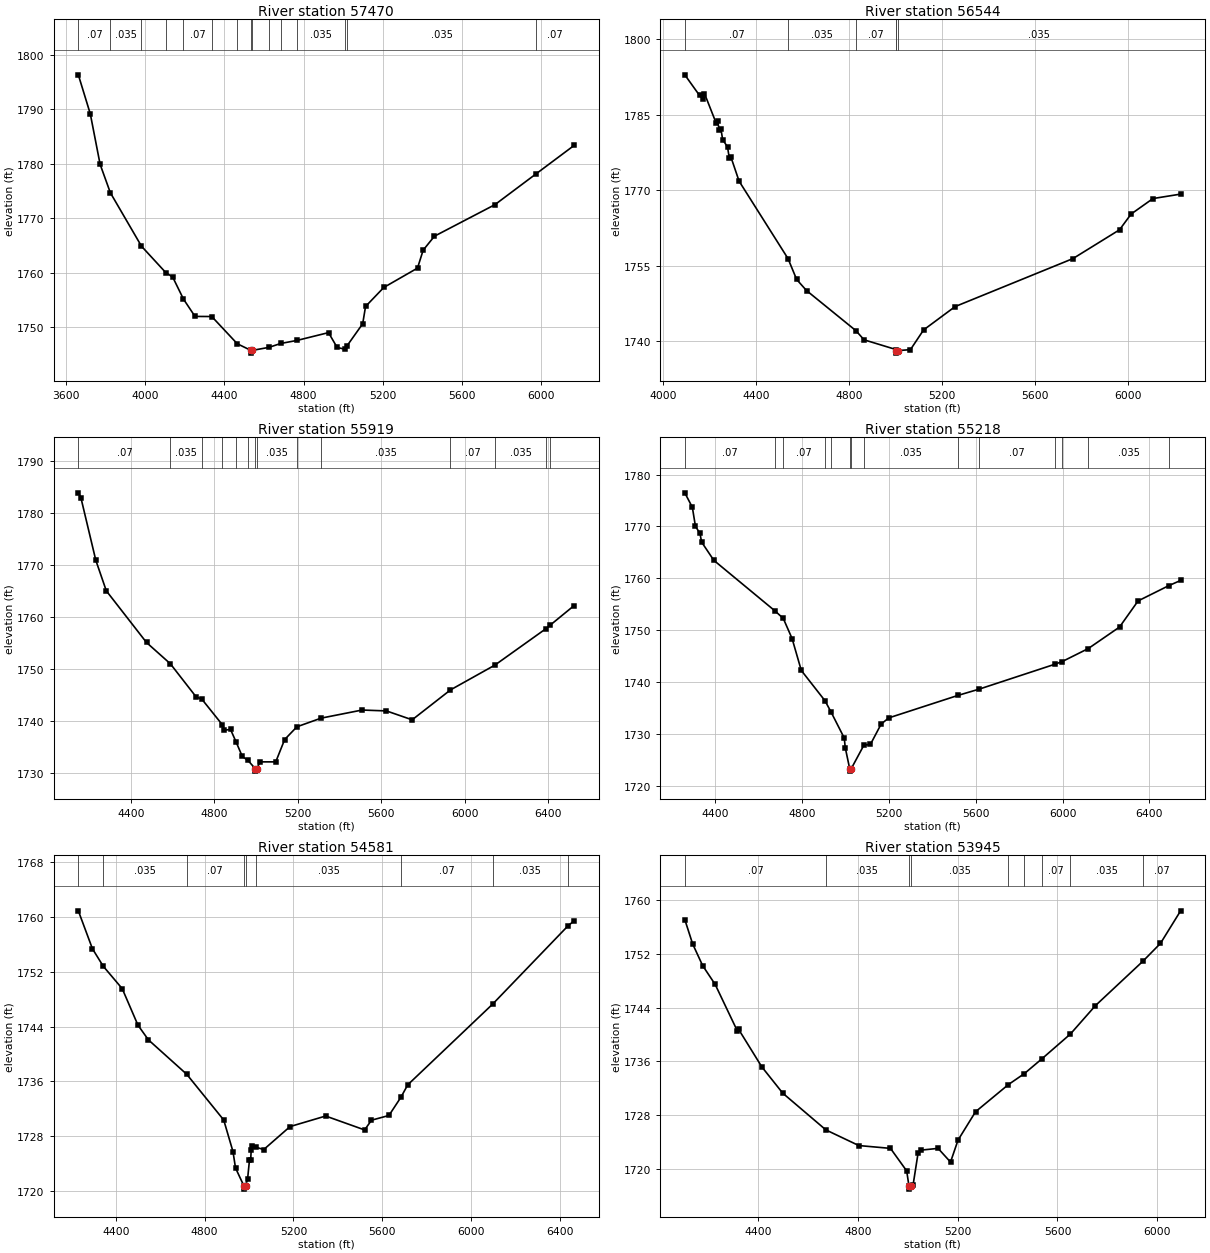
Type RM Length L Ch R = 1,57470,926,926,926
BEGIN DESCRIPTION:
Mapping XS 5e116441
END DESCRIPTION:
XS GIS Cut Line= 3
      1675617.05      6972025.39      1676276.76      6973188.58
      1677037.15      6974070.48
#Sta/Elev= 30
  3663.4 1796.28  3723.9 1789.10  3773.2 1779.88  3824.8 1774.67  3982.1 1764.85
  4104.5 1760.02  4139.6 1759.19  4193.8 1755.16  4252.1 1751.98  4336.7 1751.96
  4465.2 1746.97  4534.3 1745.75  4534.8 1745.25  4541.1 1745.75  4625.4 1746.31
  4684.7 1747.02  4768.0 1747.59  4925.7 1749.01  4969.0 1746.30  5006.4 1745.98
  5020.1 1746.64  5098.2 1750.64  5112.5 1753.80  5204.6 1757.29  5374.7 1760.84
  5403.2 1764.13  5460.2 1766.69  5765.2 1772.47  5972.1 1778.10  6165.1 1783.34
#Mann=15,-1,0
  3663.4    0.07       0  3824.8   0.035       0  3982.1    0.07       0
  4104.5   0.035       0  4193.8    0.07       0  4336.7   0.035       0
  4465.2    0.07       0  4534.3   0.035       0  4541.1    0.07       0
  4625.4   0.035       0  4684.7    0.07       0  4768.0   0.035       0
  5006.4    0.07       0  5020.1   0.035       0  5972.1    0.07       0
Bank Sta=4534.3,4541.1
Exp/Cntr=0.3,0.1

Type RM Length L Ch R = 1,56544,625,625,625
BEGIN DESCRIPTION:
Mapping XS af363246
END DESCRIPTION:
XS GIS Cut Line= 3
      1674884.86      6972478.19      1675515.05      6973131.81
      1676496.40      6973863.26
#Sta/Elev= 30
  4094.8 1792.89  4158.4 1788.79  4172.6 1788.17  4179.5 1789.18  4229.2 1783.36
  4236.1 1783.65  4243.3 1781.85  4250.3 1782.11  4257.5 1780.06  4278.6 1778.57
  4285.8 1776.44  4292.7 1776.64  4328.2 1771.80  4538.6 1756.44  4575.7 1752.30
  4618.2 1750.10  4830.9 1742.13  4865.6 1740.33  5003.0 1738.40  5003.3 1738.19
  5003.8 1737.69  5010.4 1738.19  5065.0 1738.38  5121.5 1742.29  5257.0 1746.92
  5763.7 1756.44  5963.9 1762.15  6013.9 1765.28  6107.8 1768.35  6226.7 1769.23
#Mann=6,-1,0
  4094.8    0.07       0  4538.6   0.035       0  4830.9    0.07       0
  5003.0   0.035       0  5003.3    0.07       0  5010.4   0.035       0
Bank Sta=5003.3,5010.4
Exp/Cntr=0.3,0.1

Type RM Length L Ch R = 1,55919,701,701,701
BEGIN DESCRIPTION:
Mapping XS 408d7648
END DESCRIPTION:
XS GIS Cut Line= 3
      1674452.53      6972603.14      1674952.55      6973301.08
      1675732.99      6974604.42
#Sta/Elev= 30
  4147.9 1783.86  4160.4 1782.89  4231.6 1770.91  4282.0 1765.03  4474.8 1755.10
  4589.2 1751.01  4711.9 1744.69  4741.0 1744.17  4838.9 1739.27  4848.2 1738.25
  4877.7 1738.39  4904.7 1735.96  4934.2 1733.20  4961.6 1732.43  4995.7 1730.88
  4996.2 1730.38  5002.9 1730.88  5020.7 1732.16  5094.6 1732.16  5137.3 1736.45
  5196.0 1738.90  5311.9 1740.56  5508.7 1742.12  5625.4 1741.95  5748.8 1740.24
  5932.6 1745.99  6145.7 1750.76  6390.6 1757.76  6411.5 1758.46  6525.6 1762.20
#Mann=14,-1,0
  4147.9    0.07       0  4589.2   0.035       0  4741.0    0.07       0
  4838.9   0.035       0  4904.7    0.07       0  4961.6   0.035       0
  4995.7   0.035       0  5002.9   0.035       0  5196.0    0.07       0
  5311.9   0.035       0  5932.6    0.07       0  6145.7   0.035       0
  6390.6    0.07       0  6411.5   0.035       0
Bank Sta=4995.7,5002.9
Exp/Cntr=0.3,0.1

Type RM Length L Ch R = 1,55218,637,637,637
BEGIN DESCRIPTION:
Mapping XS edc5f9fe
END DESCRIPTION:
XS GIS Cut Line= 3
      1673845.76      6973058.00      1674361.40      6973589.27
      1675375.73      6974754.46
#Sta/Elev= 30
  4258.9 1776.47  4293.7 1773.68  4307.9 1770.02  4329.0 1768.63  4336.2 1766.98
  4392.7 1763.45  4676.0 1753.64  4712.8 1752.24  4753.4 1748.36  4795.8 1742.21
  4905.0 1736.37  4933.1 1734.18  4993.9 1729.17  4998.3 1727.34  5018.7 1723.29
  5019.2 1722.79  5026.4 1723.29  5084.2 1727.79  5114.6 1727.96  5164.0 1731.88
  5199.1 1733.06  5516.7 1737.38  5615.1 1738.60  5966.2 1743.43  5998.6 1743.93
  6118.8 1746.44  6262.5 1750.58  6348.0 1755.62  6489.2 1758.56  6544.1 1759.57
#Mann=14,-1,0
  4258.9    0.07       0  4676.0   0.035       0  4712.8    0.07       0
  4905.0   0.035       0  4933.1    0.07       0  5018.7    0.07       0
  5026.4    0.07       0  5084.2   0.035       0  5516.7    0.16       0
  5615.1    0.07       0  5966.2   0.035       0  5998.6    0.07       0
  6118.8   0.035       0  6489.2    0.07       0
Bank Sta=5018.7,5026.4
Exp/Cntr=0.3,0.1

Type RM Length L Ch R = 1,54581,636,636,636
BEGIN DESCRIPTION:
Mapping XS 3e509a5e
END DESCRIPTION:
XS GIS Cut Line= 3
      1673593.81      6973277.60      1673898.51      6973988.58
      1674382.32      6975364.58
#Sta/Elev= 30
  4231.5 1760.89  4294.9 1755.36  4343.5 1752.81  4429.1 1749.53  4499.8 1744.21
  4546.9 1742.06  4719.6 1737.03  4886.0 1730.36  4927.7 1725.75  4939.1 1723.36
  4976.4 1720.77  4976.9 1720.27  4984.3 1720.77  4993.5 1721.76  5002.0 1724.52
  5007.3 1724.52  5009.6 1725.91  5015.0 1726.60  5032.6 1726.37  5066.3 1726.05
  5184.6 1729.40  5345.0 1730.94  5520.3 1728.91  5551.2 1730.33  5629.8 1731.02
  5683.7 1733.68  5714.6 1735.50  6096.5 1747.27  6434.8 1758.66  6463.6 1759.45
#Mann=9,-1,0
  4231.5    0.07       0  4343.5   0.035       0  4719.6    0.07       0
  4976.4    0.07       0  4984.3    0.07       0  5032.6   0.035       0
  5683.7    0.07       0  6096.5   0.035       0  6434.8    0.07       0
Bank Sta=4976.4,4984.3
Exp/Cntr=0.3,0.1

Type RM Length L Ch R = 1,53945,654,654,654
BEGIN DESCRIPTION:
Mapping XS daa1b1e6
END DESCRIPTION:
XS GIS Cut Line= 3
      1673267.87      6973346.89      1673361.62      6974247.91
      1673447.55      6975328.62
#Sta/Elev= 30
  4104.4 1757.11  4135.7 1753.50  4175.9 1750.26  4226.4 1747.44  4314.9 1740.55
  4320.0 1740.78  4413.5 1735.17  4497.6 1731.25  4670.7 1725.78  4802.8 1723.45
  4929.9 1723.03  4995.0 1719.67  5003.9 1717.46  5004.4 1716.96  5011.8 1717.46
  5020.4 1717.52  5040.5 1722.30  5050.5 1722.76  5120.9 1723.03  5170.9 1720.99
  5201.0 1724.26  5271.2 1728.48  5403.1 1732.53  5467.4 1734.17  5538.6 1736.40
  5652.0 1740.06  5752.7 1744.30  5942.9 1750.90  6013.5 1753.56  6094.4 1758.41
#Mann=9,-1,0
  4104.4    0.07       0  4670.7   0.035       0  5003.9   0.035       0
  5011.8   0.035       0  5403.1    0.07       0  5467.4   0.035       0
  5538.6    0.07       0  5652.0   0.035       0  5942.9    0.07       0
Bank Sta=5003.9,5011.8
Exp/Cntr=0.3,0.1

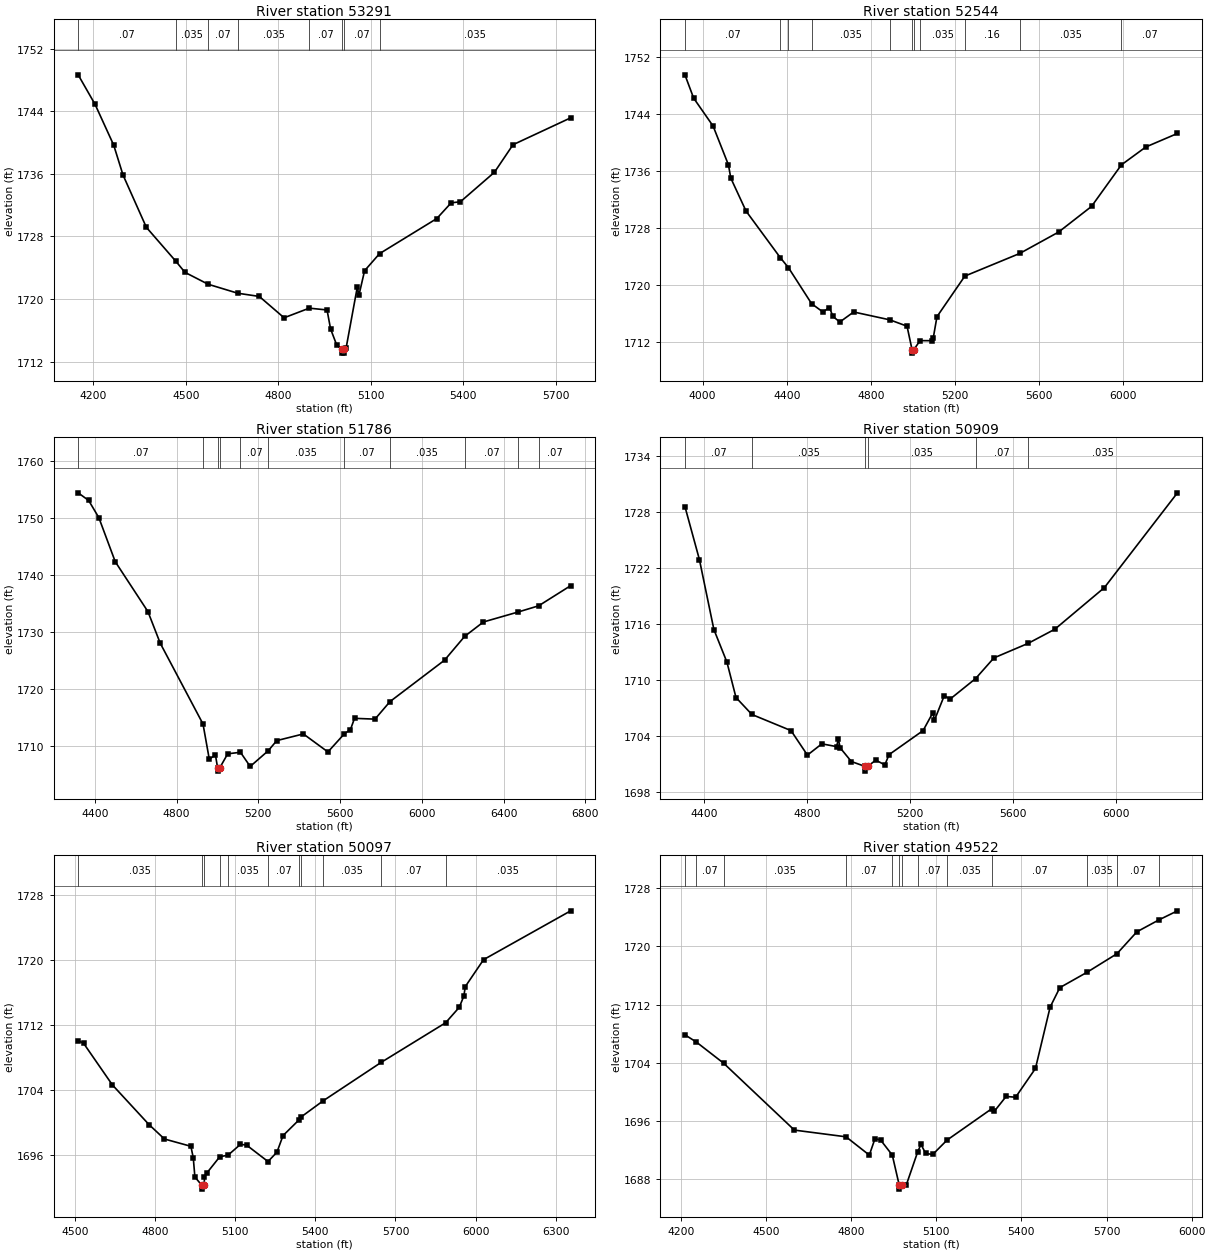
Type RM Length L Ch R = 1,53291,747,747,747
BEGIN DESCRIPTION:
Mapping XS cec0900c
END DESCRIPTION:
XS GIS Cut Line= 3
      1672872.54      6973393.32      1672785.73      6974241.87
      1672844.20      6974984.60
#Sta/Elev= 30
  4151.0 1748.67  4206.0 1744.88  4266.3 1739.68  4296.4 1735.87  4372.2 1729.17
  4468.5 1724.80  4497.5 1723.41  4572.6 1721.89  4668.8 1720.74  4738.7 1720.33
  4819.1 1717.60  4900.8 1718.83  4958.5 1718.60  4969.9 1716.18  4990.0 1714.10
  5006.0 1713.58  5006.5 1713.08  5013.8 1713.08  5014.3 1713.58  5020.2 1713.70
  5056.8 1721.56  5061.8 1720.46  5080.3 1723.62  5128.8 1725.80  5314.6 1730.29
  5361.2 1732.30  5391.3 1732.44  5501.6 1736.21  5561.8 1739.73  5749.0 1743.17
#Mann=8,-1,0
  4151.0    0.07       0  4468.5   0.035       0  4572.6    0.07       0
  4668.8   0.035       0  4900.8    0.07       0  5006.0    0.07       0
  5014.3    0.07       0  5128.8   0.035       0
Bank Sta=5006,5014.3
Exp/Cntr=0.3,0.1

Type RM Length L Ch R = 1,52544,758,758,758
BEGIN DESCRIPTION:
Mapping XS f6fc4760
END DESCRIPTION:
XS GIS Cut Line= 3
      1671799.18      6972999.72      1672111.69      6974048.38
      1672566.56      6975208.13
#Sta/Elev= 30
  3916.3 1749.55  3957.8 1746.27  4050.2 1742.34  4123.2 1736.87  4134.1 1735.03
  4206.7 1730.38  4369.3 1723.83  4408.3 1722.41  4518.4 1717.34  4571.9 1716.18
  4603.2 1716.81  4619.2 1715.56  4652.3 1714.77  4718.0 1716.18  4890.3 1715.07
  4971.6 1714.18  4995.3 1710.89  4995.8 1710.39  5003.8 1710.89  5033.8 1712.15
  5089.4 1712.14  5096.1 1712.51  5113.8 1715.52  5246.3 1721.23  5506.6 1724.41
  5691.4 1727.42  5848.0 1731.03  5990.0 1736.88  6106.3 1739.40  6256.3 1741.30
#Mann=11,-1,0
  3916.3    0.07       0  4369.3   0.035       0  4408.3    0.07       0
  4518.4   0.035       0  4890.3    0.07       0  4995.3    0.07       0
  5003.8    0.07       0  5033.8   0.035       0  5246.3    0.16       0
  5506.6   0.035       0  5990.0    0.07       0
Bank Sta=4995.3,5003.8
Exp/Cntr=0.3,0.1

Type RM Length L Ch R = 1,51786,877,877,877
BEGIN DESCRIPTION:
Mapping XS d50c1b23
END DESCRIPTION:
XS GIS Cut Line= 3
      1671389.47      6973256.67      1671382.52      6973944.21
      1671444.96      6975664.70
#Sta/Elev= 30
  4318.6 1754.41  4369.9 1753.07  4419.9 1750.04  4499.9 1742.32  4659.9 1733.55
  4719.9 1728.01  4929.3 1713.81  4960.0 1707.63  4990.0 1708.39  5001.1 1706.04
  5001.6 1705.54  5010.0 1706.04  5050.0 1708.58  5112.4 1708.85  5160.1 1706.36
  5248.3 1709.12  5290.1 1710.90  5420.2 1712.07  5540.3 1708.91  5621.2 1712.11
  5650.4 1712.83  5670.4 1714.81  5770.5 1714.67  5843.9 1717.75  6110.7 1725.02
  6209.1 1729.20  6300.8 1731.73  6472.4 1733.50  6571.1 1734.57  6727.8 1738.11
#Mann=11,-1,0
  4318.6    0.07       0  4929.3   0.035       0  5001.1   0.035       0
  5010.0   0.035       0  5112.4    0.07       0  5248.3   0.035       0
  5621.2    0.07       0  5843.9   0.035       0  6209.1    0.07       0
  6472.4   0.035       0  6571.1    0.07       0
Bank Sta=5001.1,5010
Exp/Cntr=0.3,0.1

Type RM Length L Ch R = 1,50909,812,812,812
BEGIN DESCRIPTION:
Mapping XS 64ccbb03
END DESCRIPTION:
XS GIS Cut Line= 3
      1670212.36      6973581.68      1670646.41      6974102.54
      1671222.81      6975192.84
#Sta/Elev= 30
  4326.2 1728.59  4382.5 1722.89  4438.6 1715.39  4489.2 1711.89  4524.4 1708.09
  4586.1 1706.27  4737.9 1704.54  4801.6 1701.91  4857.6 1703.12  4914.9 1702.82
  4921.4 1703.62  4929.2 1702.67  4972.2 1701.22  5025.9 1700.69  5026.4 1700.19
  5034.8 1700.69  5066.9 1701.37  5102.0 1700.86  5118.4 1701.96  5250.4 1704.54
  5288.8 1706.48  5294.4 1705.65  5332.8 1708.30  5354.8 1707.91  5454.5 1710.13
  5525.2 1712.34  5657.9 1713.90  5761.7 1715.42  5954.1 1719.89  6237.5 1730.06
#Mann=6,-1,0
  4326.2    0.07       0  4586.1   0.035       0  5025.9   0.035       0
  5034.8   0.035       0  5454.5    0.07       0  5657.9   0.035       0
Bank Sta=5025.9,5034.8
Exp/Cntr=0.3,0.1

Type RM Length L Ch R = 1,50097,575,575,575
BEGIN DESCRIPTION:
Mapping XS 2dc74303
END DESCRIPTION:
XS GIS Cut Line= 3
      1669677.65      6973987.95      1669948.49      6974390.74
      1670528.37      6975619.94
#Sta/Elev= 30
  4511.6 1710.04  4531.7 1709.73  4639.7 1704.59  4776.8 1699.70  4834.7 1697.92
  4933.7 1697.02  4942.7 1695.60  4948.7 1693.24  4973.9 1692.24  4974.4 1691.74
  4983.5 1692.24  4984.7 1693.22  4992.3 1693.68  5041.9 1695.73  5073.0 1695.93
  5119.4 1697.26  5142.2 1697.17  5222.6 1695.14  5256.1 1696.30  5278.8 1698.34
  5339.7 1700.31  5347.5 1700.66  5428.8 1702.62  5647.5 1707.39  5887.7 1712.25
  5938.7 1714.15  5955.9 1715.53  5961.4 1716.71  6029.8 1720.03  6356.1 1726.05
#Mann=11,-1,0
  4511.6   0.035       0  4973.9   0.035       0  4983.5   0.035       0
  5041.9    0.07       0  5073.0   0.035       0  5222.6    0.07       0
  5339.7   0.035       0  5347.5    0.07       0  5428.8   0.035       0
  5647.5    0.07       0  5887.7   0.035       0
Bank Sta=4973.9,4983.5
Exp/Cntr=0.3,0.1

Type RM Length L Ch R = 1,49522,663,663,663
BEGIN DESCRIPTION:
Swager Creek 82.0
END DESCRIPTION:
XS GIS Cut Line= 3
      1669566.55      6974052.22      1669655.00      6974838.00
      1669896.40      6975751.81
#Sta/Elev= 30
  4214.1 1707.85  4254.8 1706.84  4350.5 1703.95  4599.9 1694.77  4781.9 1693.85
  4864.0 1691.34  4884.1 1693.61  4904.2 1693.39  4945.0 1691.34  4969.7 1687.17
  4970.2 1686.67  4979.6 1687.17  4994.8 1687.29  5034.8 1691.82  5046.2 1692.80
  5062.7 1691.56  5087.6 1691.43  5138.0 1693.40  5295.8 1697.71  5304.8 1697.36
  5346.2 1699.39  5379.6 1699.28  5449.6 1703.23  5501.3 1711.65  5535.5 1714.32
  5631.5 1716.43  5736.7 1718.97  5807.0 1721.98  5884.9 1723.62  5950.0 1724.86
#Mann=13,-1,0
  4214.1   0.035       0  4254.8    0.07       0  4350.5   0.035       0
  4781.9    0.07       0  4945.0   0.035       0  4969.7   0.035       0
  4979.6   0.035       0  5034.8    0.07       0  5138.0   0.035       0
  5295.8    0.07       0  5631.5   0.035       0  5736.7    0.07       0
  5884.9   0.035       0
Bank Sta=4969.7,4979.6
Exp/Cntr=0.3,0.1