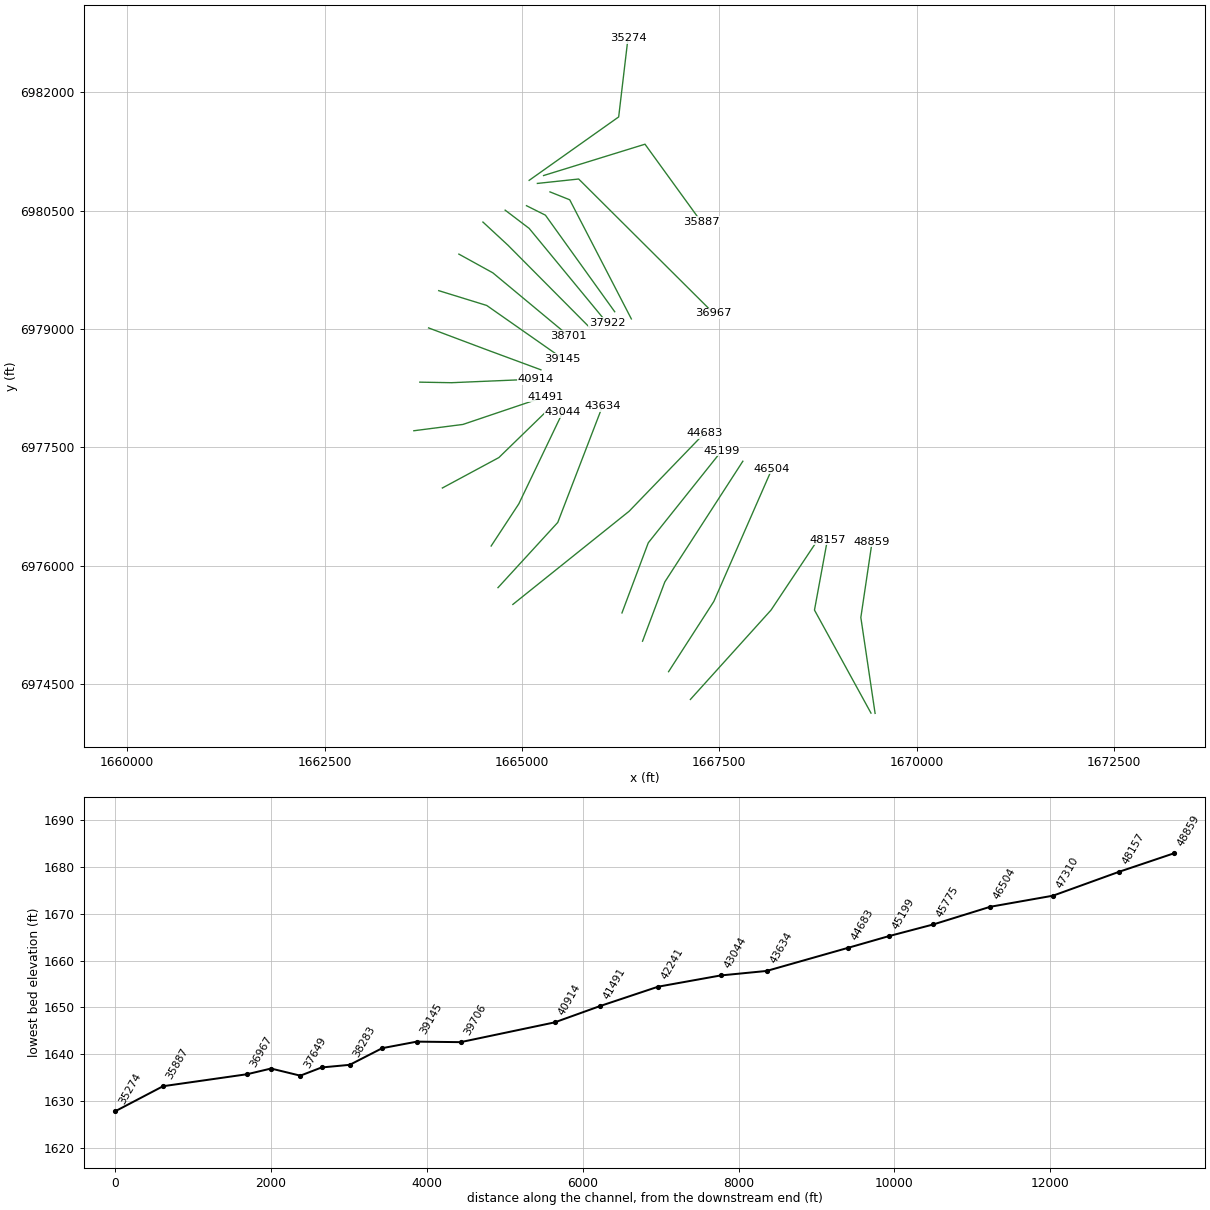
HEC-RAS study Swager Creek.prj: Swager Creek Base Level Engineering

--- Swager Creek.g01 (geometry) --- (continued)

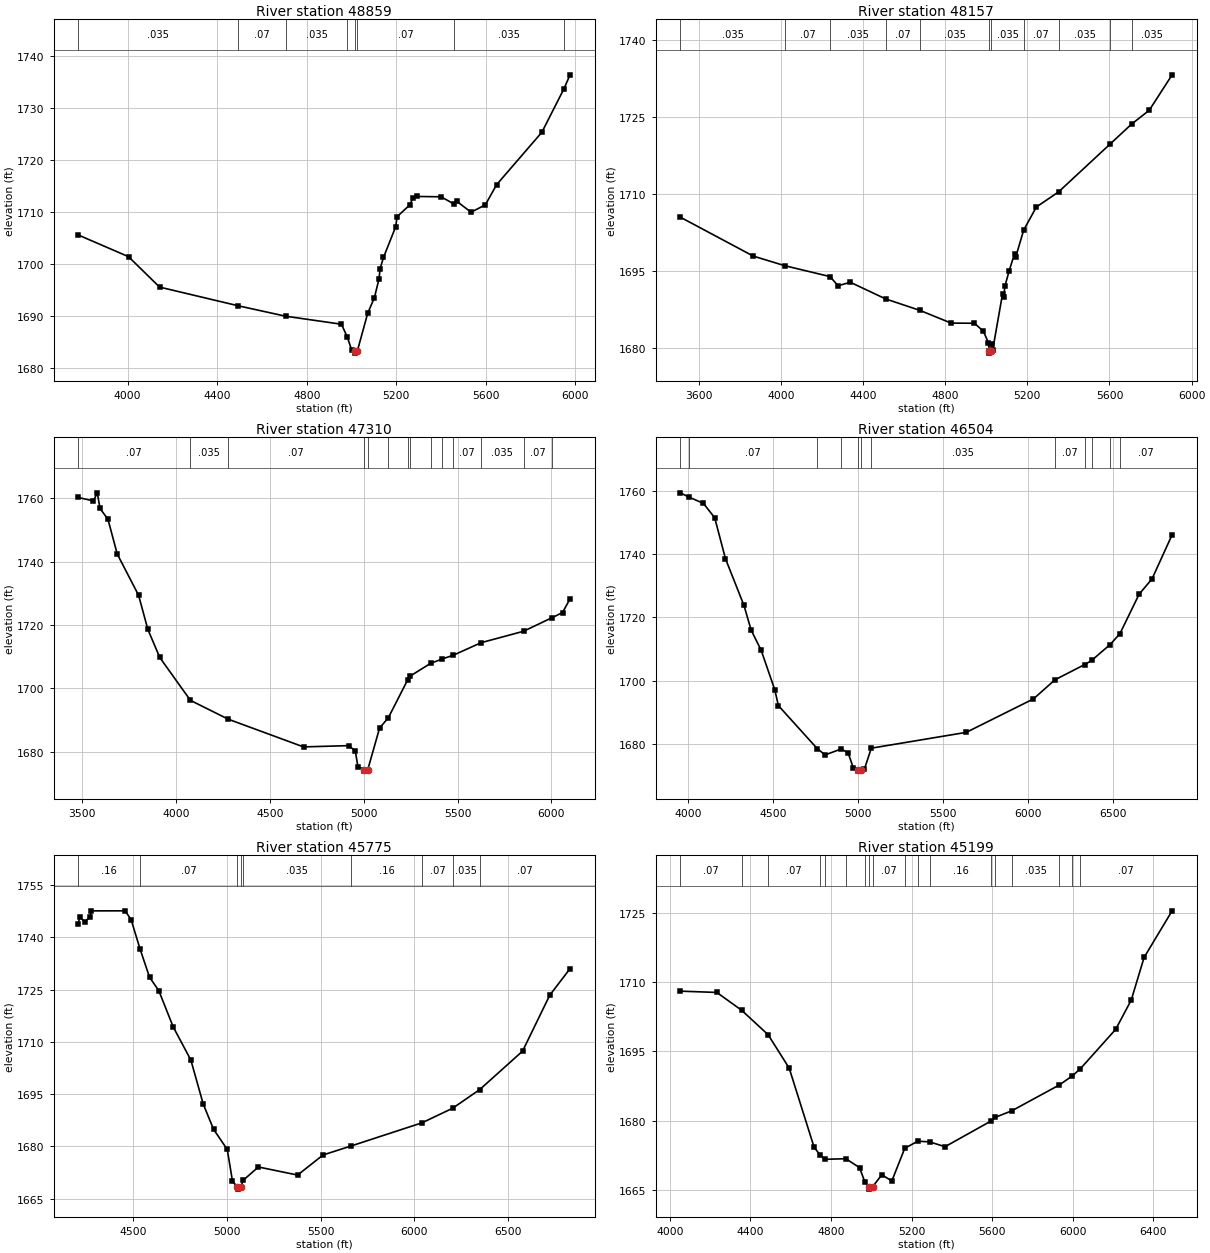
Type RM Length L Ch R = 1,48859,702,702,702
BEGIN DESCRIPTION:
Mapping XS fd823527
END DESCRIPTION:
XS GIS Cut Line= 3
      1669472.80      6974128.56      1669292.24      6975343.86
      1669434.61      6976302.21
#Sta/Elev= 30
  3778.7 1705.56  4003.8 1701.38  4142.6 1695.54  4495.0 1691.94  4705.5 1689.95
  4955.2 1688.41  4981.6 1685.90  5001.4 1683.37  5016.6 1683.36  5017.1 1682.86
  5026.7 1683.36  5072.2 1690.49  5102.5 1693.53  5122.7 1697.09  5128.0 1699.11
  5142.9 1701.23  5197.4 1707.12  5203.6 1709.06  5261.7 1711.37  5274.4 1712.74
  5294.6 1712.94  5400.6 1712.88  5457.7 1711.49  5470.0 1712.02  5534.3 1709.92
  5597.9 1711.33  5648.4 1715.21  5850.6 1725.28  5949.7 1733.67  5976.2 1736.30
#Mann=8,-1,0
  3778.7   0.035       0  4495.0    0.07       0  4705.5   0.035       0
  4981.6    0.07       0  5016.6    0.07       0  5026.7    0.07       0
  5457.7   0.035       0  5949.7    0.07       0
Bank Sta=5016.6,5026.7
Exp/Cntr=0.3,0.1

Type RM Length L Ch R = 1,48157,847,847,847
BEGIN DESCRIPTION:
Swager Creek 81.0
END DESCRIPTION:
XS GIS Cut Line= 3
      1669420.73      6974132.03      1668705.00      6975438.00
      1668868.69      6976327.73
#Sta/Elev= 30
  3511.0 1705.42  3865.9 1697.84  4019.8 1695.96  4239.7 1693.84  4279.3 1692.06
  4338.8 1692.73  4510.6 1689.49  4678.5 1687.24  4829.2 1684.78  4942.9 1684.75
  4986.5 1683.19  5010.4 1680.98  5015.4 1679.43  5015.9 1678.93  5025.7 1679.43
  5026.8 1680.64  5031.8 1679.58  5079.8 1690.53  5084.9 1689.94  5091.7 1692.07
  5112.1 1695.01  5138.0 1698.30  5143.0 1697.56  5182.5 1702.90  5244.1 1707.39
  5352.4 1710.34  5604.0 1719.69  5708.7 1723.58  5793.3 1726.22  5904.9 1733.14
#Mann=11,-1,0
  3511.0   0.035       0  4019.8    0.07       0  4239.7   0.035       0
  4510.6    0.07       0  4678.5   0.035       0  5015.4   0.035       0
  5025.7   0.035       0  5182.5    0.07       0  5352.4   0.035       0
  5604.0    0.07       0  5708.7   0.035       0
Bank Sta=5015.4,5025.7
Exp/Cntr=0.3,0.1

Type RM Length L Ch R = 1,47310,806,806,806
BEGIN DESCRIPTION:
Swager Creek 79.0
END DESCRIPTION:
XS GIS Cut Line= 3
      1667133.45      6974305.15      1668155.00      6975438.00
      1668760.53      6976348.63
#Sta/Elev= 30
  3479.7 1760.27  3560.9 1759.20  3581.8 1761.74  3596.0 1756.83  3638.6 1753.36
  3687.9 1742.41  3801.5 1729.39  3850.9 1718.61  3914.4 1709.73  4077.6 1696.19
  4279.0 1690.24  4679.7 1681.49  4920.3 1681.89  4955.4 1680.21  4969.6 1675.20
  5003.2 1674.34  5003.7 1673.84  5022.0 1674.34  5084.8 1687.45  5131.1 1690.67
  5233.7 1702.58  5247.9 1703.87  5356.2 1707.87  5419.6 1709.30  5475.8 1710.41
  5625.4 1714.41  5851.1 1718.01  6000.2 1722.22  6058.8 1723.92  6098.7 1728.23
#Mann=14,-1,0
  3479.7    0.07       0  4077.6   0.035       0  4279.0    0.07       0
  5003.2    0.07       0  5022.0    0.07       0  5131.1   0.035       0
  5233.7    0.07       0  5247.9   0.035       0  5356.2    0.07       0
  5419.6   0.035       0  5475.8    0.07       0  5625.4   0.035       0
  5851.1    0.07       0  6000.2   0.035       0
Bank Sta=5003.2,5022
Exp/Cntr=0.3,0.1

Type RM Length L Ch R = 1,46504,729,729,729
BEGIN DESCRIPTION:
Mapping XS 09a42c74
END DESCRIPTION:
XS GIS Cut Line= 3
      1666857.13      6974657.02      1667430.03      6975546.76
      1668167.88      6977230.78
#Sta/Elev= 30
  3952.2 1759.29  4004.1 1757.93  4088.5 1755.97  4155.1 1751.42  4218.5 1738.50
  4327.5 1723.75  4369.7 1715.98  4429.1 1709.56  4509.0 1697.12  4530.2 1692.14
  4759.2 1678.56  4805.5 1676.59  4901.0 1678.48  4941.5 1677.13  4971.9 1672.41
  4998.8 1671.97  4999.3 1671.47  5017.6 1671.97  5037.2 1672.17  5077.3 1678.71
  5636.4 1683.70  6032.3 1694.26  6159.0 1700.29  6334.2 1705.10  6375.2 1706.40
  6483.3 1711.39  6541.2 1714.81  6654.9 1727.32  6730.5 1732.11  6849.0 1746.05
#Mann=12,-1,0
  3952.2   0.035       0  4004.1    0.07       0  4759.2   0.035       0
  4901.0    0.07       0  4998.8    0.07       0  5017.6    0.07       0
  5077.3   0.035       0  6159.0    0.07       0  6334.2   0.035       0
  6375.2    0.07       0  6483.3   0.035       0  6541.2    0.07       0
Bank Sta=4998.8,5017.6
Exp/Cntr=0.3,0.1

Type RM Length L Ch R = 1,45775,576,576,576
BEGIN DESCRIPTION:
Mapping XS 1db3e654
END DESCRIPTION:
XS GIS Cut Line= 3
      1666527.25      6975043.27      1666809.37      6975794.15
      1667797.90      6977324.64
#Sta/Elev= 30
  4206.5 1743.94  4215.6 1745.82  4240.5 1744.52  4270.7 1745.78  4276.1 1747.62
  4457.2 1747.63  4489.3 1745.08  4536.5 1736.71  4587.4 1728.57  4637.2 1724.66
  4713.6 1714.30  4807.9 1704.77  4873.9 1692.14  4928.9 1684.89  5002.1 1679.10
  5029.6 1670.11  5056.5 1668.21  5057.0 1667.71  5075.4 1668.21  5085.8 1670.19
  5168.0 1674.07  5377.4 1671.75  5513.3 1677.52  5662.1 1680.09  6041.4 1686.76
  6204.5 1690.94  6349.2 1696.31  6577.5 1707.34  6722.7 1723.41  6830.6 1731.01
#Mann=9,-1,0
  4206.5    0.16       0  4536.5    0.07       0  5056.5    0.07       0
  5075.4    0.07       0  5085.8   0.035       0  5662.1    0.16       0
  6041.4    0.07       0  6204.5   0.035       0  6349.2    0.07       0
Bank Sta=5056.5,5075.4
Exp/Cntr=0.3,0.1

Type RM Length L Ch R = 1,45199,516,516,516
BEGIN DESCRIPTION:
Mapping XS 26cbbb34
END DESCRIPTION:
XS GIS Cut Line= 3
      1666266.76      6975401.81      1666600.09      6976290.68
      1667530.30      6977456.92
#Sta/Elev= 30
  4051.9 1708.03  4233.4 1707.75  4356.3 1703.90  4487.6 1698.62  4592.5 1691.38
  4715.8 1674.30  4744.1 1672.67  4768.3 1671.64  4873.9 1671.77  4941.8 1669.84
  4968.3 1666.70  4987.5 1665.69  4988.0 1665.19  5006.5 1665.69  5052.3 1668.31
  5101.9 1666.94  5166.0 1674.02  5230.7 1675.56  5289.0 1675.42  5366.1 1674.37
  5596.0 1679.97  5614.4 1680.71  5698.8 1682.17  5933.3 1687.73  5998.2 1689.71
  6037.9 1691.25  6213.0 1699.77  6290.1 1706.10  6354.1 1715.34  6493.0 1725.41
#Mann=18,-1,0
  4051.9    0.07       0  4356.3   0.035       0  4487.6    0.07       0
  4744.1   0.035       0  4768.3    0.07       0  4873.9   0.035       0
  4968.3    0.07       0  4987.5    0.07       0  5006.5    0.07       0
  5166.0   0.035       0  5230.7    0.07       0  5289.0    0.16       0
  5596.0   0.035       0  5614.4    0.16       0  5698.8   0.035       0
  5933.3    0.07       0  5998.2   0.035       0  6037.9    0.07       0
Bank Sta=4987.5,5006.5
Exp/Cntr=0.3,0.1

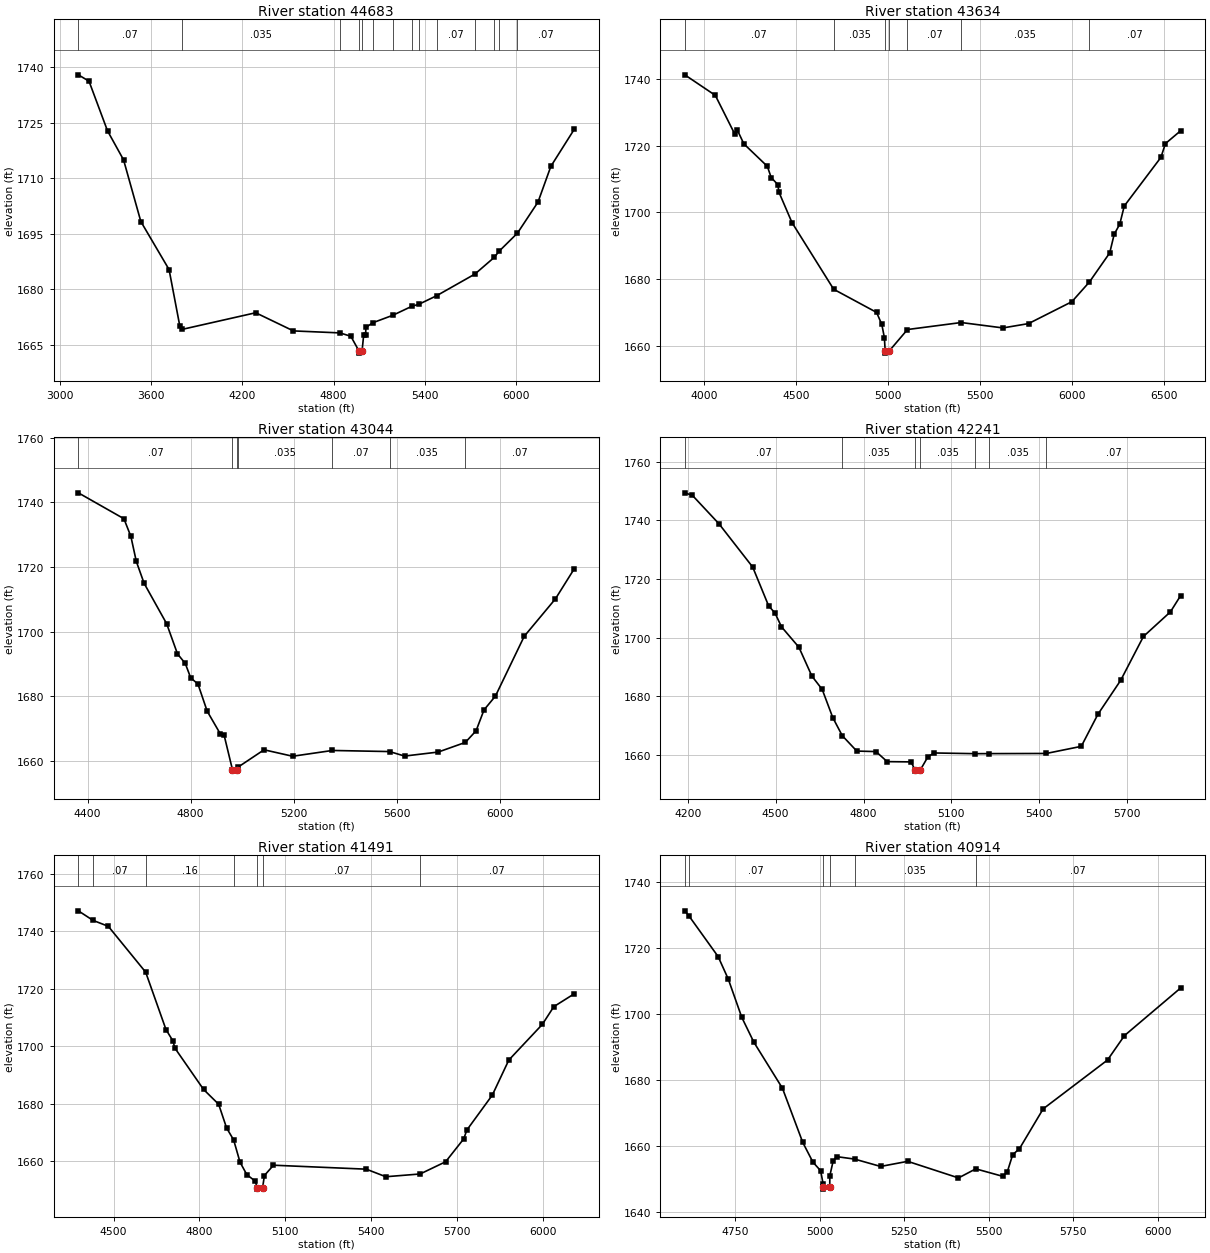
Type RM Length L Ch R = 1,44683,1049,1049,1049
BEGIN DESCRIPTION:
Mapping XS 6ed1704a
END DESCRIPTION:
XS GIS Cut Line= 3
      1664884.78      6975509.41      1666357.03      6976689.99
      1667310.93      6977678.57
#Sta/Elev= 30
  3121.2 1738.00  3191.4 1736.28  3313.1 1722.85  3418.7 1715.00  3532.3 1698.32
  3718.0 1685.33  3788.4 1670.10  3801.5 1669.13  4287.7 1673.65  4535.7 1668.74
  4841.6 1668.20  4913.4 1667.29  4967.9 1663.23  4968.4 1662.73  4987.0 1663.23
  4998.2 1667.75  5010.4 1667.61  5012.6 1669.69  5057.5 1670.94  5189.6 1672.97
  5315.7 1675.42  5360.3 1675.93  5476.9 1678.24  5729.6 1684.12  5856.6 1688.63
  5889.2 1690.32  6009.0 1695.18  6144.2 1703.58  6228.9 1713.25  6382.1 1723.23
#Mann=14,-1,0
  3121.2    0.07       0  3801.5   0.035       0  4841.6    0.07       0
  4967.9    0.07       0  4987.0    0.07       0  5057.5   0.035       0
  5189.6    0.07       0  5315.7   0.035       0  5360.3    0.16       0
  5476.9    0.07       0  5729.6   0.035       0  5856.6    0.07       0
  5889.2   0.035       0  6009.0    0.07       0
Bank Sta=4967.9,4987
Exp/Cntr=0.3,0.1

Type RM Length L Ch R = 1,43634,590,590,590
BEGIN DESCRIPTION:
Mapping XS dbf81c7c
END DESCRIPTION:
XS GIS Cut Line= 3
      1664696.62      6975721.94      1665453.56      6976548.32
      1666019.52      6978020.53
#Sta/Elev= 30
  3894.0 1741.27  4060.0 1735.11  4166.1 1723.47  4180.3 1724.64  4215.4 1720.56
  4343.1 1713.82  4364.0 1710.46  4399.8 1708.36  4406.6 1706.02  4477.5 1696.92
  4704.1 1676.94  4937.5 1670.00  4965.9 1666.40  4980.0 1662.43  4984.4 1658.28
  4984.9 1657.78  5004.0 1658.28  5105.7 1664.86  5398.0 1666.96  5625.0 1665.34
  5764.3 1666.64  6000.0 1673.20  6095.9 1679.14  6206.0 1687.84  6230.6 1693.48
  6260.6 1696.44  6285.3 1701.92  6484.6 1716.50  6509.2 1720.64  6591.9 1724.49
#Mann=7,-1,0
  3894.0    0.07       0  4704.1   0.035       0  4984.4   0.035       0
  5004.0   0.035       0  5105.7    0.07       0  5398.0   0.035       0
  6095.9    0.07       0
Bank Sta=4984.4,5004
Exp/Cntr=0.3,0.1

Type RM Length L Ch R = 1,43044,803,803,803
BEGIN DESCRIPTION:
Mapping XS df80b7a2
END DESCRIPTION:
XS GIS Cut Line= 3
      1664609.83      6976249.74      1664960.50      6976784.43
      1665515.78      6977943.57
#Sta/Elev= 30
  4364.2 1742.89  4541.2 1734.88  4568.2 1729.40  4589.3 1721.66  4619.5 1714.91
  4707.0 1702.42  4749.1 1693.08  4779.3 1690.12  4800.4 1685.67  4828.5 1683.76
  4864.4 1675.35  4914.9 1668.40  4930.0 1667.97  4962.3 1657.32  4962.8 1656.82
  4981.9 1657.32  4984.2 1658.06  5085.2 1663.42  5196.1 1661.42  5350.3 1663.21
  5572.3 1662.87  5630.7 1661.48  5761.2 1662.72  5866.4 1665.70  5908.2 1669.30
  5939.0 1675.76  5983.3 1680.03  6095.1 1698.52  6216.2 1710.10  6288.9 1719.35
#Mann=7,-1,0
  4364.2    0.07       0  4962.3   0.035       0  4981.9    0.07       0
  4984.2   0.035       0  5350.3    0.07       0  5572.3   0.035       0
  5866.4    0.07       0
Bank Sta=4962.3,4981.9
Exp/Cntr=0.3,0.1

Type RM Length L Ch R = 1,42241,750,750,750
BEGIN DESCRIPTION:
Mapping XS 817a2b56
END DESCRIPTION:
XS GIS Cut Line= 3
      1663992.12      6976985.14      1664707.38      6977370.54
      1665338.25      6977984.08
#Sta/Elev= 30
  4190.0 1749.44  4216.0 1748.57  4306.6 1738.87  4421.8 1724.09  4476.1 1710.86
  4498.0 1708.38  4519.9 1703.71  4579.5 1696.72  4623.7 1686.89  4659.0 1682.32
  4695.1 1672.70  4727.5 1666.53  4777.0 1661.27  4842.7 1661.09  4880.8 1657.66
  4962.8 1657.57  4974.9 1654.92  4975.4 1654.42  4994.5 1654.92  5020.2 1659.36
  5041.3 1660.62  5181.4 1660.38  5228.8 1660.40  5423.9 1660.45  5543.4 1662.88
  5600.0 1673.80  5677.9 1685.42  5755.6 1700.40  5847.7 1708.80  5882.5 1714.34
#Mann=7,-1,0
  4190.0    0.07       0  4727.5   0.035       0  4974.9   0.035       0
  4994.5   0.035       0  5181.4    0.07       0  5228.8   0.035       0
  5423.9    0.07       0
Bank Sta=4974.9,4994.5
Exp/Cntr=0.3,0.1

Type RM Length L Ch R = 1,41491,577,577,577
BEGIN DESCRIPTION:
Mapping XS a1b63e1f
END DESCRIPTION:
XS GIS Cut Line= 3
      1663631.02      6977710.82      1664252.52      6977790.68
      1665300.54      6978144.65
#Sta/Elev= 30
  4377.1 1747.06  4428.4 1743.74  4481.9 1741.67  4612.4 1725.73  4683.6 1705.72
  4708.4 1701.71  4713.8 1699.42  4814.7 1684.94  4867.5 1679.78  4895.3 1671.52
  4919.9 1667.37  4942.1 1659.65  4965.9 1655.30  4996.1 1652.97  5001.4 1650.76
  5001.9 1650.26  5021.1 1650.76  5027.4 1655.00  5059.1 1658.58  5383.5 1657.20
  5451.7 1654.57  5571.6 1655.53  5660.7 1659.78  5724.1 1667.76  5734.8 1670.80
  5823.9 1682.97  5881.5 1695.15  5998.5 1707.54  6038.8 1713.73  6109.9 1718.18
#Mann=7,-1,0
  4377.1   0.035       0  4428.4    0.07       0  4612.4    0.16       0
  4919.9    0.07       0  5001.4    0.07       0  5021.1    0.07       0
  5571.6    0.07       0
Bank Sta=5001.4,5021.1
Exp/Cntr=0.3,0.1

Type RM Length L Ch R = 1,40914,1208,1208,1208
BEGIN DESCRIPTION:
Mapping XS 8798a50d
END DESCRIPTION:
XS GIS Cut Line= 3
      1663706.49      6978326.56      1664105.76      6978319.62
      1665170.87      6978364.72
#Sta/Elev= 30
  4601.5 1731.23  4613.4 1729.74  4700.0 1717.35  4730.0 1710.52  4770.0 1698.89
  4805.7 1691.36  4890.1 1677.41  4950.1 1660.98  4980.1 1655.01  5003.0 1652.38
  5010.1 1648.49  5010.2 1647.31  5010.7 1646.81  5029.9 1647.31  5030.1 1650.85
  5040.1 1655.40  5050.1 1656.67  5103.4 1655.92  5180.2 1653.69  5260.3 1655.24
  5410.4 1650.21  5461.5 1652.96  5540.6 1650.71  5554.5 1652.01  5570.6 1657.25
  5590.6 1659.08  5660.7 1671.16  5850.8 1685.97  5900.9 1693.38  6066.9 1707.82
#Mann=6,-1,0
  4601.5    0.16       0  4613.4    0.07       0  5010.2    0.07       0
  5029.9    0.07       0  5103.4   0.035       0  5461.5    0.07       0
Bank Sta=5010.2,5029.9
Exp/Cntr=0.3,0.1

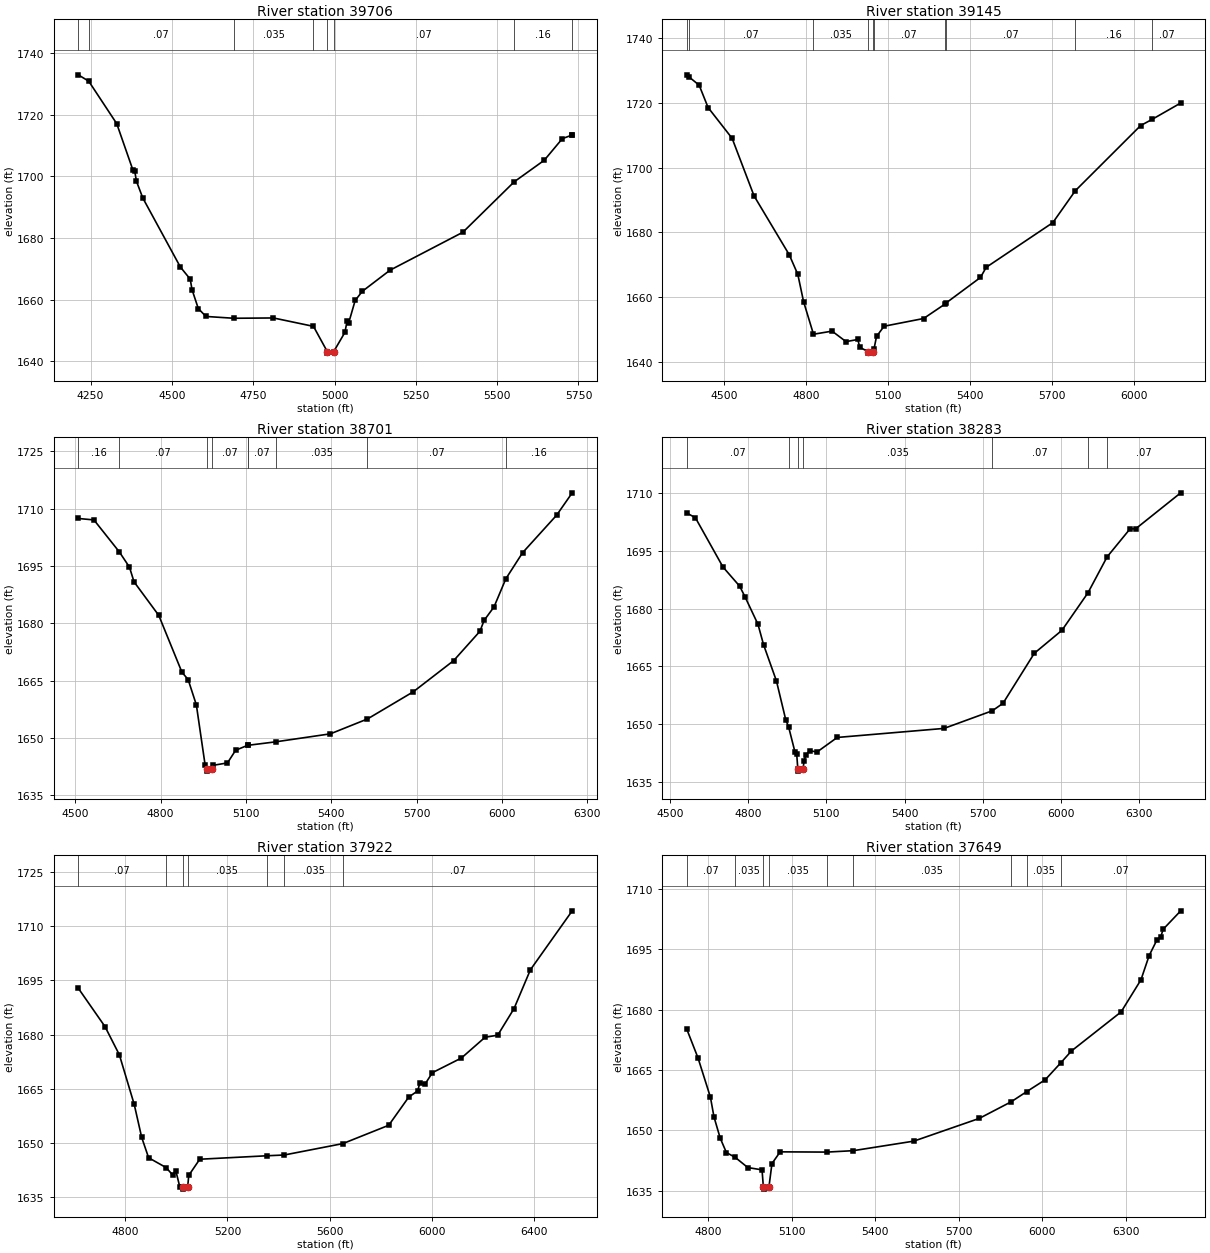
Type RM Length L Ch R = 1,39706,561,561,561
BEGIN DESCRIPTION:
Mapping XS 4a67ac03
END DESCRIPTION:
XS GIS Cut Line= 3
      1663817.55      6979014.06      1664546.73      6978739.76
      1665240.31      6978483.13
#Sta/Elev= 30
  4212.1 1732.96  4244.3 1730.90  4330.5 1717.09  4380.3 1702.00  4385.6 1701.83
  4391.0 1698.42  4410.5 1692.98  4526.0 1670.56  4556.3 1666.62  4561.9 1663.22
  4581.2 1657.06  4604.7 1654.50  4690.5 1653.91  4812.3 1654.01  4935.3 1651.28
  4977.7 1643.09  4978.2 1642.59  4997.5 1643.09  5032.0 1649.35  5038.4 1652.92
  5043.7 1652.47  5063.4 1659.68  5085.3 1662.65  5170.6 1669.52  5394.5 1681.84
  5552.5 1698.23  5644.8 1705.22  5700.3 1712.23  5728.7 1713.35  5730.7 1713.46
#Mann=8,-1,0
  4212.1    0.16       0  4244.3    0.07       0  4690.5   0.035       0
  4935.3    0.07       0  4977.7    0.07       0  4997.5    0.07       0
  5552.5    0.16       0  5728.7    0.07       0
Bank Sta=4977.7,4997.5
Exp/Cntr=0.3,0.1

Type RM Length L Ch R = 1,39145,444,444,444
BEGIN DESCRIPTION:
Mapping XS b0b92525
END DESCRIPTION:
XS GIS Cut Line= 3
      1663946.06      6979486.28      1664553.67      6979298.78
      1665515.46      6978625.18
#Sta/Elev= 30
  4362.5 1728.62  4370.3 1728.01  4408.0 1725.42  4440.7 1718.52  4528.8 1709.01
  4609.2 1691.23  4738.1 1673.07  4769.5 1667.01  4790.5 1658.63  4826.9 1648.53
  4895.1 1649.49  4946.2 1646.25  4989.3 1646.91  4996.5 1644.49  5026.7 1643.20
  5027.2 1642.70  5046.5 1643.20  5048.5 1643.90  5057.9 1647.85  5085.5 1651.00
  5230.5 1653.39  5307.6 1657.78  5310.9 1658.07  5438.8 1666.06  5459.8 1669.19
  5703.9 1682.98  5786.5 1692.85  6025.6 1712.95  6067.4 1714.85  6172.6 1719.92
#Mann=10,-1,0
  4362.5    0.16       0  4370.3    0.07       0  4826.9   0.035       0
  5026.7   0.035       0  5046.5   0.035       0  5048.5    0.07       0
  5307.6   0.035       0  5310.9    0.07       0  5786.5    0.16       0
  6067.4    0.07       0
Bank Sta=5026.7,5046.5
Exp/Cntr=0.3,0.1

Type RM Length L Ch R = 1,38701,418,418,418
BEGIN DESCRIPTION:
Mapping XS 703a3413
END DESCRIPTION:
XS GIS Cut Line= 3
      1664201.22      6979949.41      1664630.93      6979712.41
      1665589.27      6978915.53
#Sta/Elev= 30
  4510.1 1707.42  4565.3 1707.04  4654.6 1698.67  4690.2 1694.69  4706.3 1690.84
  4793.4 1682.05  4874.8 1667.18  4896.5 1665.28  4925.5 1658.64  4956.1 1643.00
  4961.3 1641.81  4961.8 1641.31  4981.2 1641.81  4983.6 1642.82  5034.9 1643.46
  5063.6 1646.77  5106.1 1648.07  5106.4 1648.06  5204.0 1648.97  5396.9 1651.07
  5527.2 1654.96  5688.5 1662.08  5830.4 1670.23  5922.9 1677.92  5937.2 1680.73
  5972.3 1684.29  6013.8 1691.64  6072.6 1698.45  6192.4 1708.28  6247.2 1714.13
#Mann=9,-1,0
  4510.1    0.16       0  4654.6    0.07       0  4961.3    0.07       0
  4981.2    0.07       0  5106.1   0.035       0  5106.4    0.07       0
  5204.0   0.035       0  5527.2    0.07       0  6013.8    0.16       0
Bank Sta=4961.3,4981.2
Exp/Cntr=0.3,0.1

Type RM Length L Ch R = 1,38283,361,361,361
BEGIN DESCRIPTION:
Mapping XS f4abe965
END DESCRIPTION:
XS GIS Cut Line= 3
      1664505.93      6980355.64      1664821.04      6980063.97
      1665854.54      6979022.66
#Sta/Elev= 30
  4563.7 1704.82  4596.8 1703.60  4702.8 1690.78  4766.8 1685.81  4787.8 1682.99
  4837.2 1675.89  4858.7 1670.58  4908.0 1661.19  4943.7 1651.12  4954.8 1649.24
  4978.9 1642.79  4985.7 1642.32  4990.2 1638.25  4990.7 1637.75  5010.1 1638.25
  5014.3 1640.46  5021.3 1641.94  5035.4 1643.08  5063.7 1642.71  5141.5 1646.50
  5551.6 1648.85  5736.8 1653.43  5777.9 1655.37  5898.1 1668.37  6004.2 1674.34
  6104.1 1684.08  6177.7 1693.43  6265.8 1700.71  6287.0 1700.70  6460.2 1710.06
#Mann=7,-1,0
  4563.7    0.07       0  4954.8   0.035       0  4990.2   0.035       0
  5010.1   0.035       0  5736.8    0.07       0  6104.1    0.16       0
  6177.7    0.07       0
Bank Sta=4990.2,5010.1
Exp/Cntr=0.3,0.1

Type RM Length L Ch R = 1,37922,273,273,273
BEGIN DESCRIPTION:
Mapping XS 173768b2
END DESCRIPTION:
XS GIS Cut Line= 3
      1664787.21      6980506.66      1665091.87      6980274.91
      1666076.27      6979079.56
#Sta/Elev= 30
  4616.9 1692.85  4721.5 1682.21  4777.7 1674.39  4835.8 1660.65  4864.9 1651.54
  4892.0 1645.88  4960.2 1643.17  4985.5 1641.17  4998.5 1642.26  5013.8 1637.84
  5024.7 1637.69  5025.2 1637.19  5044.6 1637.69  5049.0 1641.00  5092.0 1645.47
  5354.8 1646.43  5422.3 1646.64  5651.5 1649.80  5830.9 1654.88  5909.0 1662.67
  5944.2 1664.41  5952.1 1666.53  5972.9 1666.28  6001.6 1669.45  6114.9 1673.50
  6207.5 1679.25  6257.0 1679.83  6320.8 1687.20  6384.7 1697.94  6548.2 1714.27
#Mann=7,-1,0
  4616.9    0.07       0  4960.2   0.035       0  5024.7   0.035       0
  5044.6   0.035       0  5354.8    0.07       0  5422.3   0.035       0
  5651.5    0.07       0
Bank Sta=5024.7,5044.6
Exp/Cntr=0.3,0.1

Type RM Length L Ch R = 1,37649,376,376,376
BEGIN DESCRIPTION:
Mapping XS 2becb8bd
END DESCRIPTION:
XS GIS Cut Line= 3
      1665057.56      6980562.90      1665297.16      6980443.10
      1666174.79      6979219.11
#Sta/Elev= 30
  4722.6 1675.15  4763.0 1668.00  4807.7 1658.23  4820.4 1653.36  4842.7 1648.10
  4865.1 1644.50  4896.1 1643.35  4941.9 1640.79  4993.0 1640.22  4997.8 1635.94
  4998.3 1635.44  5017.7 1635.94  5028.6 1641.78  5058.1 1644.69  5226.2 1644.63
  5320.5 1644.98  5538.2 1647.35  5772.9 1652.98  5887.2 1657.09  5942.8 1659.60
  6009.9 1662.57  6066.2 1666.80  6104.2 1669.72  6282.5 1679.41  6353.8 1687.37
  6383.2 1693.38  6411.8 1697.36  6425.0 1698.08  6433.6 1699.92  6496.6 1704.49
#Mann=9,-1,0
  4722.6    0.07       0  4896.1   0.035       0  4997.8   0.035       0
  5017.7   0.035       0  5226.2    0.07       0  5320.5   0.035       0
  5887.2    0.07       0  5942.8   0.035       0  6066.2    0.07       0
Bank Sta=4997.8,5017.7
Exp/Cntr=0.3,0.1

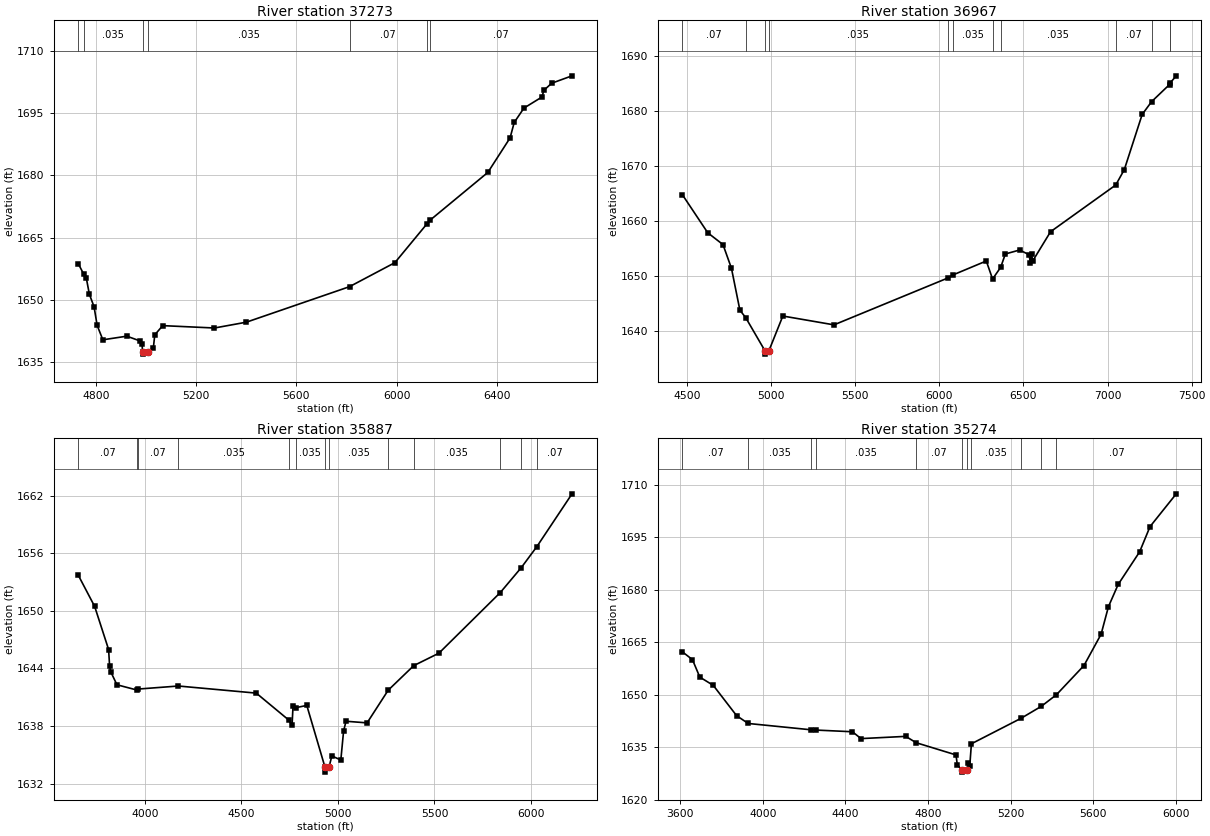
Type RM Length L Ch R = 1,37273,306,306,306
BEGIN DESCRIPTION:
Swager Creek 62.0
END DESCRIPTION:
XS GIS Cut Line= 3
      1665355.04      6980737.98      1665605.00      6980638.00
      1666385.70      6979128.00
#Sta/Elev= 30
  4730.3 1658.76  4751.8 1656.25  4762.6 1655.25  4774.7 1651.38  4793.5 1648.34
  4805.7 1643.88  4828.5 1640.41  4924.1 1641.28  4978.0 1640.11  4984.7 1639.40
  4986.9 1637.46  4987.4 1636.96  5006.8 1637.46  5029.9 1638.47  5035.5 1641.60
  5067.1 1643.82  5273.5 1643.25  5400.7 1644.65  5812.1 1653.20  5993.0 1658.98
  6119.5 1668.22  6133.8 1669.23  6363.8 1680.71  6452.4 1689.02  6468.9 1692.74
  6507.6 1696.19  6579.7 1698.87  6586.8 1700.45  6618.3 1702.18  6699.4 1703.96
#Mann=7,-1,0
  4730.3    0.07       0  4751.8   0.035       0  4986.9   0.035       0
  5006.8   0.035       0  5812.1    0.07       0  6119.5   0.035       0
  6133.8    0.07       0
Bank Sta=4986.9,5006.8
Exp/Cntr=0.3,0.1

Type RM Length L Ch R = 1,36967,1080,1080,1080
BEGIN DESCRIPTION:
Mapping XS 8aba9dcb
END DESCRIPTION:
XS GIS Cut Line= 3
      1665195.53      6980845.42      1665718.56      6980901.24
      1667425.17      6979201.72
#Sta/Elev= 30
  4474.0 1664.76  4624.3 1657.85  4714.8 1655.70  4765.1 1651.39  4815.4 1643.74
  4849.4 1642.42  4966.4 1636.25  4966.9 1635.75  4986.3 1636.25  5070.5 1642.69
  5374.5 1641.08  6053.2 1649.64  6082.9 1650.19  6279.6 1652.71  6316.9 1649.43
  6365.2 1651.56  6392.8 1653.99  6477.6 1654.71  6534.2 1653.85  6541.3 1652.40
  6548.3 1654.00  6555.4 1652.71  6661.5 1658.04  7049.0 1666.55  7099.9 1669.36
  7206.0 1679.40  7261.8 1681.72  7368.7 1684.85  7372.7 1685.15  7408.5 1686.43
#Mann=12,-1,0
  4474.0    0.07       0  4849.4   0.035       0  4966.4   0.035       0
  4986.3   0.035       0  6053.2    0.07       0  6082.9   0.035       0
  6316.9    0.07       0  6365.2   0.035       0  7049.0    0.07       0
  7261.8   0.035       0  7368.7    0.07       0  7372.7   0.035       0
Bank Sta=4966.4,4986.3
Exp/Cntr=0.3,0.1

Type RM Length L Ch R = 1,35887,613,613,613
BEGIN DESCRIPTION:
Mapping XS 0513d031
END DESCRIPTION:
XS GIS Cut Line= 3
      1665273.70      6980945.26      1666558.38      6981342.38
      1667270.08      6980359.45
#Sta/Elev= 30
  3654.3 1653.71  3739.4 1650.45  3811.7 1645.96  3816.9 1644.20  3823.1 1643.63
  3854.8 1642.29  3958.8 1641.74  3962.5 1641.84  4173.4 1642.16  4576.7 1641.42
  4744.7 1638.62  4762.0 1638.06  4767.2 1640.08  4781.1 1639.90  4838.4 1640.14
  4932.9 1633.69  4933.4 1633.19  4953.3 1633.69  4968.2 1634.88  5014.7 1634.45
  5029.1 1637.48  5041.7 1638.49  5150.8 1638.32  5260.0 1641.72  5392.3 1644.28
  5522.9 1645.58  5841.1 1651.90  5949.9 1654.50  6030.3 1656.68  6212.5 1662.18
#Mann=13,-1,0
  3654.3    0.07       0  3958.8   0.035       0  3962.5    0.07       0
  4173.4   0.035       0  4744.7    0.07       0  4781.1   0.035       0
  4932.9   0.035       0  4953.3   0.035       0  5260.0    0.07       0
  5392.3   0.035       0  5841.1    0.07       0  5949.9   0.035       0
  6030.3    0.07       0
Bank Sta=4932.9,4953.3
Exp/Cntr=0.3,0.1

Type RM Length L Ch R = 1,35274,685,685,685
BEGIN DESCRIPTION:
Swager Creek 60.0
END DESCRIPTION:
XS GIS Cut Line= 3
      1665091.35      6980884.47      1666225.06      6981688.20
      1666342.80      6982684.27
#Sta/Elev= 30
  3610.3 1662.25  3658.7 1660.03  3694.3 1655.04  3759.6 1652.67  3872.7 1644.00
  3928.8 1641.77  4235.2 1639.95  4258.8 1639.88  4433.8 1639.40  4475.6 1637.44
  4692.2 1638.08  4742.5 1636.27  4935.8 1632.77  4942.0 1629.96  4965.3 1628.35
  4965.8 1627.85  4989.9 1628.35  4992.4 1630.60  5002.4 1629.58  5010.4 1635.96
  5250.7 1643.24  5349.5 1646.69  5422.7 1650.01  5555.9 1658.35  5638.8 1667.30
  5674.5 1675.20  5721.7 1681.56  5825.5 1690.87  5875.9 1698.09  6003.0 1707.47
#Mann=11,-1,0
  3610.3    0.07       0  3928.8   0.035       0  4235.2    0.07       0
  4258.8   0.035       0  4742.5    0.07       0  4965.3    0.07       0
  4989.9    0.07       0  5010.4   0.035       0  5250.7    0.07       0
  5349.5   0.035       0  5422.7    0.07       0
Bank Sta=4965.3,4989.9
Exp/Cntr=0.3,0.1