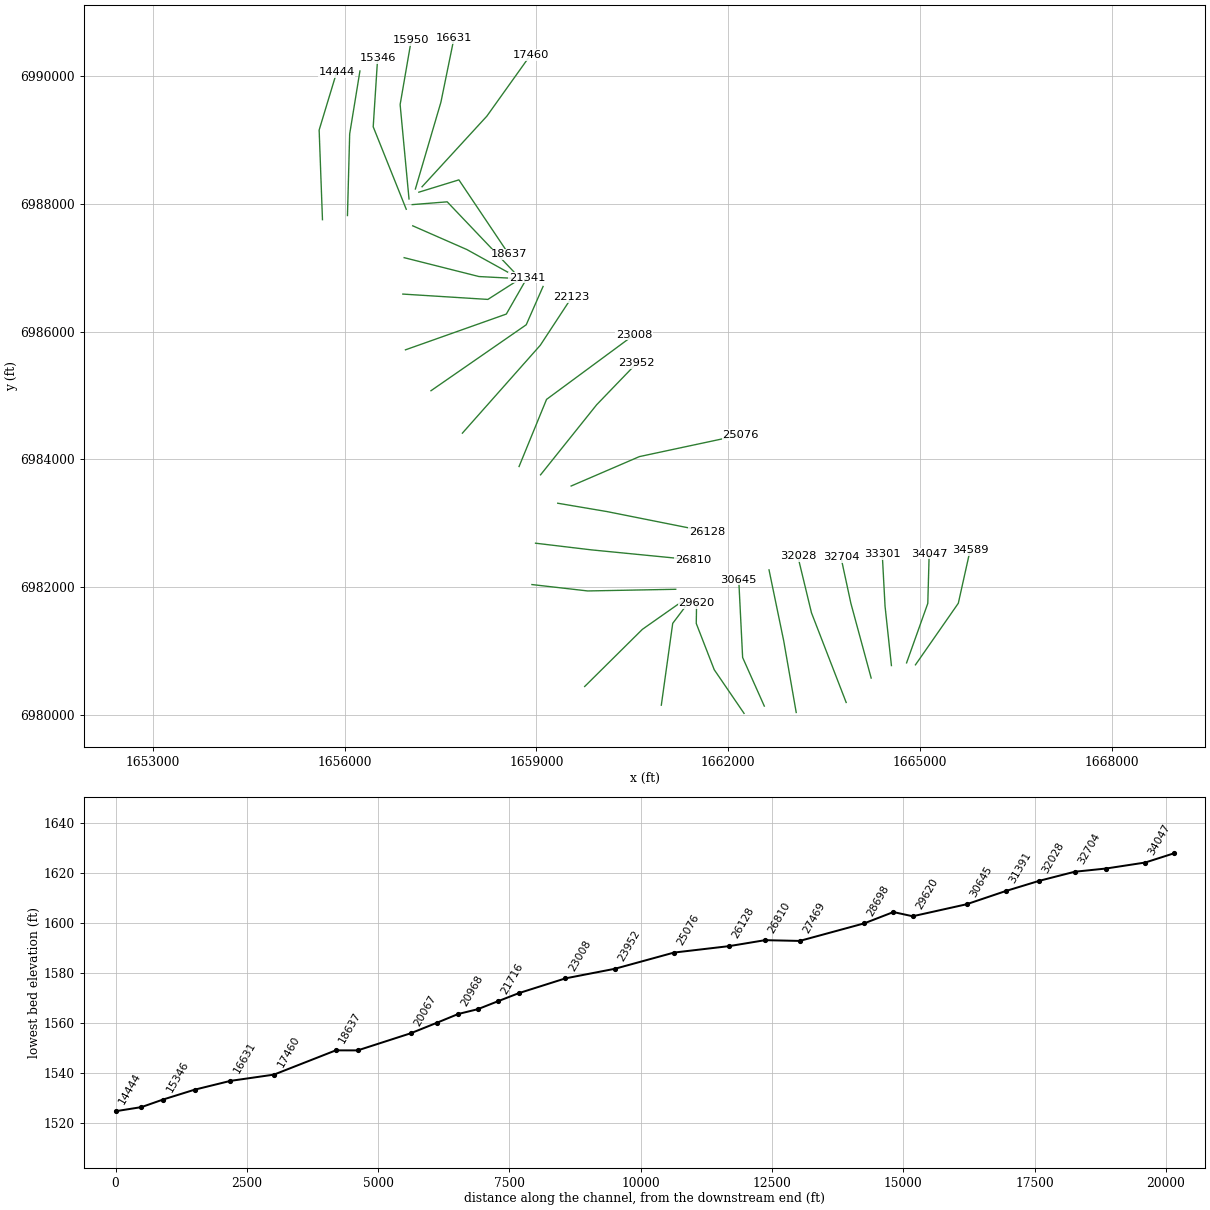
HEC-RAS study Swager Creek.prj: Swager Creek Base Level Engineering

--- Swager Creek.g01 (geometry) --- (continued)

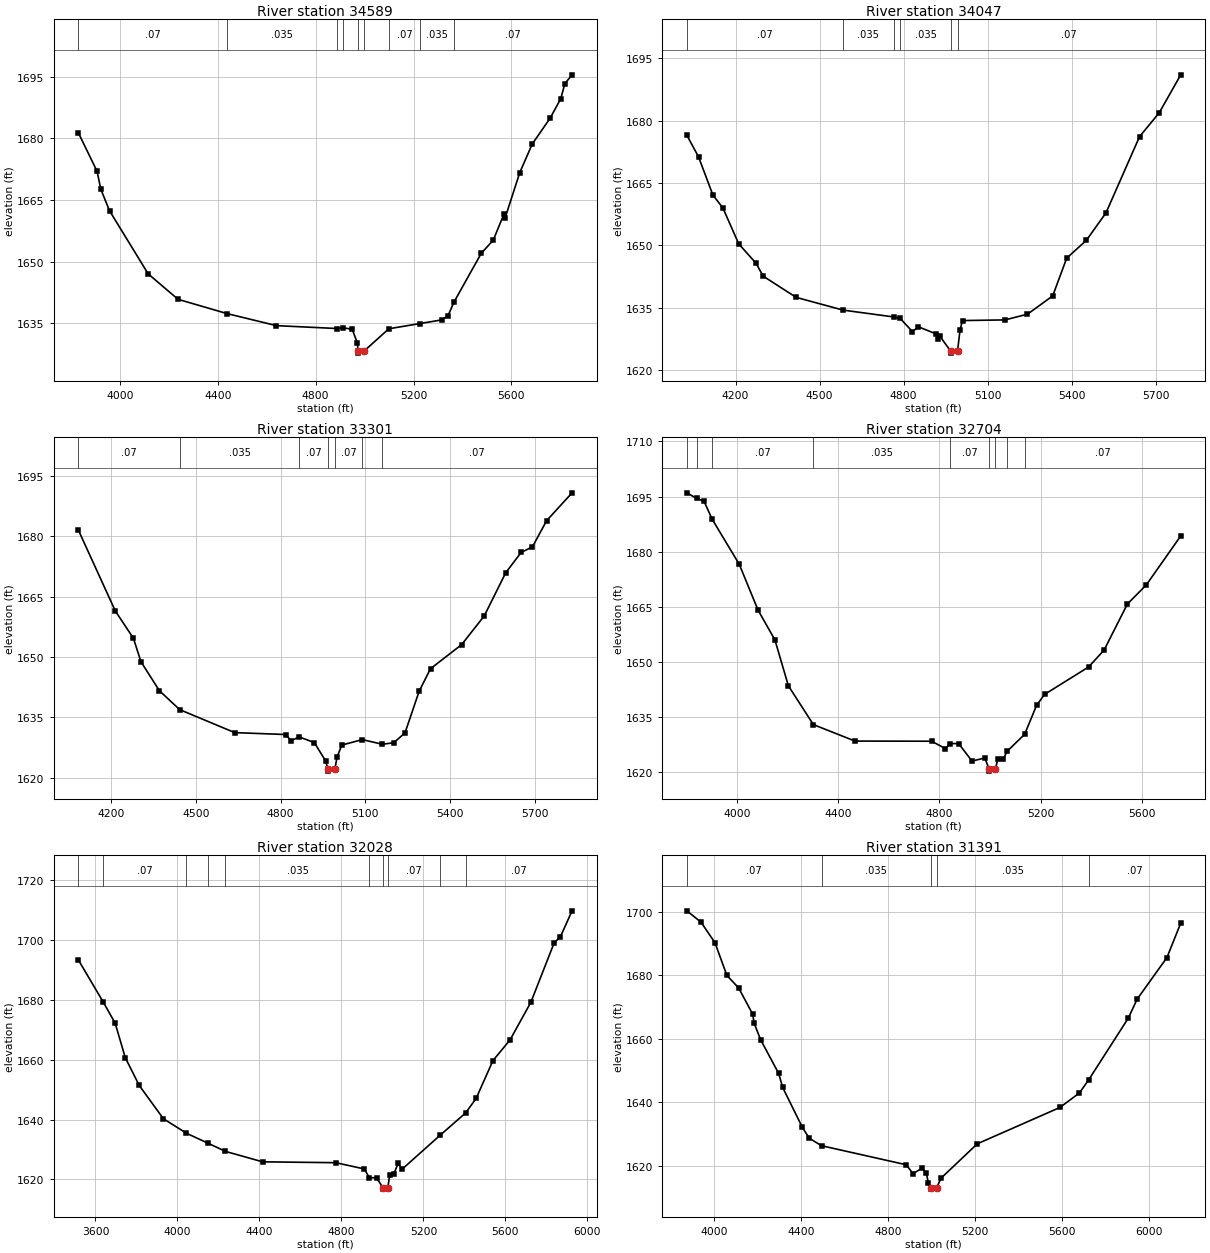
Type RM Length L Ch R = 1,34589,542,542,542
BEGIN DESCRIPTION:
Mapping XS 24a57def
END DESCRIPTION:
XS GIS Cut Line= 3
      1664926.41      6980788.96      1665596.43      6981751.58
      1665780.22      6982576.92
#Sta/Elev= 30
  3829.7 1681.44  3906.9 1671.97  3921.7 1667.67  3957.5 1662.39  4115.5 1646.99
  4237.6 1640.79  4438.9 1637.29  4640.0 1634.37  4886.6 1633.67  4912.3 1633.85
  4949.4 1633.48  4970.8 1630.12  4973.3 1628.17  4973.8 1627.67  4997.9 1628.17
  5099.3 1633.61  5227.4 1634.89  5316.5 1635.78  5341.5 1636.84  5364.9 1640.05
  5477.1 1652.02  5525.8 1655.20  5569.3 1661.50  5574.4 1660.62  5634.1 1671.64
  5685.3 1678.65  5758.6 1684.96  5802.1 1689.71  5818.5 1693.36  5848.1 1695.51
#Mann=9,-1,0
  3829.7    0.07       0  4438.9   0.035       0  4886.6    0.07       0
  4912.3   0.035       0  4973.3   0.035       0  4997.9   0.035       0
  5099.3    0.07       0  5227.4   0.035       0  5364.9    0.07       0
Bank Sta=4973.3,4997.9
Exp/Cntr=0.3,0.1

Type RM Length L Ch R = 1,34047,746,746,746
BEGIN DESCRIPTION:
Mapping XS 4f42bff7
END DESCRIPTION:
XS GIS Cut Line= 3
      1664787.55      6980819.39      1665119.29      6981749.85
      1665140.94      6982524.92
#Sta/Elev= 30
  4026.2 1676.49  4067.9 1671.27  4118.9 1662.13  4155.0 1658.95  4211.3 1650.34
  4273.0 1645.68  4298.5 1642.57  4416.4 1637.45  4583.8 1634.39  4764.7 1632.74
  4788.0 1632.37  4831.6 1629.20  4852.8 1630.37  4916.5 1628.64  4924.3 1627.33
  4929.6 1628.08  4967.9 1624.53  4968.4 1624.03  4992.6 1624.53  5001.4 1629.62
  5010.4 1631.87  5162.2 1632.03  5242.3 1633.41  5332.3 1637.81  5382.3 1646.91
  5452.4 1651.18  5522.4 1657.79  5642.4 1676.16  5712.5 1681.89  5789.4 1691.04
#Mann=6,-1,0
  4026.2    0.07       0  4583.8   0.035       0  4764.7    0.07       0
  4788.0   0.035       0  4967.9    0.07       0  4992.6    0.07       0
Bank Sta=4967.9,4992.6
Exp/Cntr=0.3,0.1

Type RM Length L Ch R = 1,33301,597,597,597
BEGIN DESCRIPTION:
Mapping XS 0fd024be
END DESCRIPTION:
XS GIS Cut Line= 3
      1664550.71      6980777.62      1664450.88      6981706.44
      1664407.48      6982518.11
#Sta/Elev= 30
  4084.3 1681.66  4215.4 1661.48  4279.5 1654.68  4306.0 1648.87  4371.5 1641.63
  4443.3 1636.93  4637.9 1631.22  4818.9 1630.74  4836.8 1629.20  4866.0 1630.15
  4919.5 1628.73  4959.7 1624.15  4967.5 1622.14  4968.0 1621.64  4992.2 1622.14
  4999.9 1625.14  5016.7 1628.12  5089.2 1629.48  5160.5 1628.32  5200.3 1628.70
  5240.3 1631.15  5290.4 1641.52  5330.5 1647.11  5440.6 1653.10  5520.7 1660.25
  5596.3 1670.94  5650.9 1676.02  5691.0 1677.41  5741.1 1683.91  5831.3 1690.85
#Mann=7,-1,0
  4084.3    0.07       0  4443.3   0.035       0  4866.0    0.07       0
  4967.5    0.07       0  4992.2    0.07       0  5089.2   0.035       0
  5160.5    0.07       0
Bank Sta=4967.5,4992.2
Exp/Cntr=0.3,0.1

Type RM Length L Ch R = 1,32704,676,676,676
BEGIN DESCRIPTION:
Mapping XS e2a77d14
END DESCRIPTION:
XS GIS Cut Line= 3
      1664233.86      6980582.35      1663917.03      6981749.85
      1663760.97      6982473.79
#Sta/Elev= 30
  3802.5 1696.00  3841.4 1694.46  3870.5 1693.68  3902.8 1688.76  4009.3 1676.58
  4083.7 1664.10  4150.3 1656.00  4203.2 1643.56  4302.0 1633.00  4466.3 1628.52
  4769.3 1628.48  4823.8 1626.46  4840.7 1627.83  4875.6 1627.84  4928.6 1623.08
  4979.2 1623.93  4996.3 1620.85  4996.8 1620.35  5021.1 1620.85  5030.8 1623.78
  5051.3 1623.52  5066.8 1625.71  5136.5 1630.37  5183.5 1638.23  5214.9 1641.20
  5388.8 1648.65  5450.2 1653.26  5542.3 1665.79  5617.0 1670.98  5752.8 1684.27
#Mann=9,-1,0
  3802.5    0.07       0  3841.4    0.16       0  3902.8    0.07       0
  4302.0   0.035       0  4840.7    0.07       0  4996.3    0.07       0
  5021.1    0.07       0  5066.8   0.035       0  5136.5    0.07       0
Bank Sta=4996.3,5021.1
Exp/Cntr=0.3,0.1

Type RM Length L Ch R = 1,32028,637,637,637
BEGIN DESCRIPTION:
Mapping XS aa4e0ecf
END DESCRIPTION:
XS GIS Cut Line= 3
      1663843.23      6980200.41      1663300.71      6981602.28
      1663088.08      6982483.19
#Sta/Elev= 30
  3516.0 1693.46  3636.4 1679.48  3696.1 1672.25  3745.3 1660.73  3813.7 1651.39
  3931.6 1640.26  4044.1 1635.41  4148.0 1632.11  4234.4 1629.34  4415.5 1625.85
  4772.6 1625.56  4911.5 1623.47  4936.6 1620.53  4971.7 1620.53  5001.8 1617.22
  5002.3 1616.72  5026.6 1617.22  5035.4 1621.35  5055.9 1621.83  5076.5 1625.31
  5097.1 1623.44  5280.3 1634.67  5405.9 1642.20  5457.1 1647.05  5539.4 1659.71
  5622.9 1666.65  5724.6 1679.26  5837.8 1699.07  5868.6 1701.16  5925.4 1709.81
#Mann=10,-1,0
  3516.0    0.16       0  3636.4    0.07       0  4044.1   0.035       0
  4148.0    0.07       0  4234.4   0.035       0  4936.6    0.07       0
  5001.8    0.07       0  5026.6    0.07       0  5280.3   0.035       0
  5405.9    0.07       0
Bank Sta=5001.8,5026.6
Exp/Cntr=0.3,0.1

Type RM Length L Ch R = 1,31391,746,746,746
BEGIN DESCRIPTION:
Mapping XS b86fb2a0
END DESCRIPTION:
XS GIS Cut Line= 3
      1663062.00      6980044.09      1662866.68      6981163.91
      1662636.85      6982274.04
#Sta/Elev= 30
  3875.9 1700.33  3940.7 1696.77  4005.3 1690.25  4059.8 1679.97  4113.3 1676.10
  4178.9 1667.72  4184.4 1665.07  4214.9 1659.72  4298.0 1649.09  4316.4 1644.67
  4407.0 1632.08  4438.2 1628.70  4494.9 1626.33  4884.8 1620.32  4915.3 1617.53
  4955.9 1619.19  4976.2 1617.88  4986.3 1614.50  4999.7 1613.15  5000.2 1612.65
  5024.7 1613.15  5044.0 1616.08  5210.8 1626.92  5591.0 1638.38  5680.6 1642.95
  5722.6 1647.03  5905.3 1666.53  5946.1 1672.52  6082.7 1685.58  6146.3 1696.44
#Mann=5,-1,0
  3875.9    0.07       0  4494.9   0.035       0  4999.7   0.035       0
  5024.7   0.035       0  5722.6    0.07       0
Bank Sta=4999.7,5024.7
Exp/Cntr=0.3,0.1

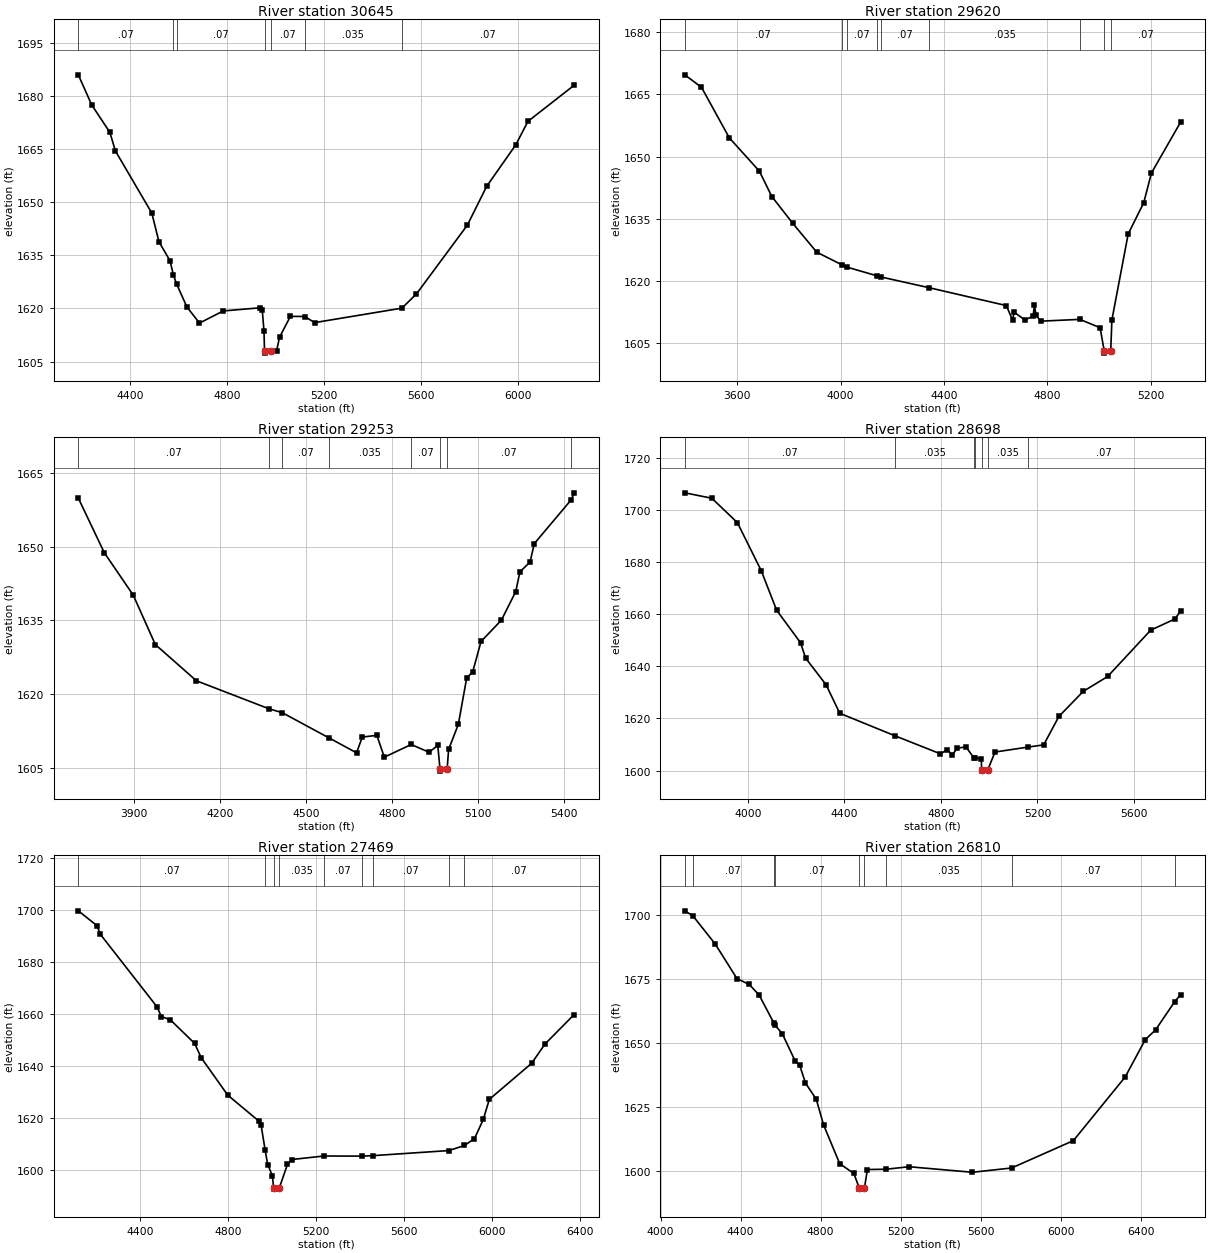
Type RM Length L Ch R = 1,30645,1025,1025,1025
BEGIN DESCRIPTION:
Mapping XS f1fe10da
END DESCRIPTION:
XS GIS Cut Line= 3
      1662562.86      6980143.94      1662224.32      6980903.49
      1662163.56      6982118.79
#Sta/Elev= 30
  4185.4 1686.01  4240.3 1677.56  4315.5 1669.77  4338.7 1664.49  4489.1 1646.93
  4518.3 1638.86  4564.2 1633.47  4577.7 1629.57  4591.0 1626.97  4633.9 1620.42
  4685.9 1615.86  4784.2 1619.29  4934.6 1620.17  4945.3 1619.51  4952.3 1613.68
  4954.7 1607.87  4955.2 1607.37  4979.7 1607.87  5004.3 1607.98  5016.7 1611.86
  5061.5 1617.77  5120.7 1617.71  5161.7 1615.99  5522.0 1620.08  5582.2 1624.09
  5792.5 1643.53  5872.6 1654.53  5992.7 1666.23  6042.8 1672.86  6233.8 1683.07
#Mann=7,-1,0
  4185.4    0.07       0  4577.7    0.16       0  4591.0    0.07       0
  4954.7    0.07       0  4979.7    0.07       0  5120.7   0.035       0
  5522.0    0.07       0
Bank Sta=4954.7,4979.7
Exp/Cntr=0.3,0.1

Type RM Length L Ch R = 1,29620,367,367,367
BEGIN DESCRIPTION:
Mapping XS 915762d3
END DESCRIPTION:
XS GIS Cut Line= 4
      1662246.55      6980030.02      1661780.00      6980713.00
      1661499.16      6981435.95      1661504.34      6981750.81
#Sta/Elev= 30
  3397.3 1669.71  3461.8 1666.70  3569.5 1654.51  3685.5 1646.50  3734.0 1640.36
  3814.7 1633.90  3907.4 1626.95  4003.8 1623.92  4024.3 1623.34  4140.7 1621.23
  4156.5 1620.95  4342.7 1618.36  4640.7 1614.06  4665.3 1610.53  4670.6 1612.47
  4712.5 1610.60  4744.2 1611.49  4749.6 1614.14  4755.5 1611.75  4774.1 1610.30
  4925.0 1610.73  5003.5 1608.72  5019.5 1603.09  5020.0 1602.59  5044.6 1603.09
  5049.1 1610.59  5112.1 1631.33  5172.1 1638.85  5202.1 1646.04  5314.9 1658.31
#Mann=9,-1,0
  3397.3    0.07       0  4003.8   0.035       0  4024.3    0.07       0
  4140.7   0.035       0  4156.5    0.07       0  4342.7   0.035       0
  4925.0    0.07       0  5019.5    0.07       0  5044.6    0.07       0
Bank Sta=5019.5,5044.6
Exp/Cntr=0.3,0.1

Type RM Length L Ch R = 1,29253,555,555,555
BEGIN DESCRIPTION:
Mapping XS b87e72bb
END DESCRIPTION:
XS GIS Cut Line= 3
      1660952.87      6980158.58      1661131.16      6981437.73
      1661393.29      6981784.48
#Sta/Elev= 30
  3707.7 1659.93  3798.0 1648.81  3899.0 1640.14  3975.7 1630.08  4118.8 1622.69
  4371.4 1616.98  4417.5 1616.19  4581.5 1611.01  4676.4 1608.00  4696.3 1611.22
  4747.1 1611.56  4772.9 1607.11  4866.5 1609.70  4928.8 1608.12  4959.1 1609.52
  4966.7 1604.77  4967.2 1604.27  4991.8 1604.77  4996.8 1608.69  5030.7 1613.81
  5059.8 1623.28  5080.6 1624.49  5109.7 1630.71  5180.5 1635.04  5230.5 1640.87
  5245.0 1644.89  5280.4 1646.90  5295.0 1650.65  5423.7 1659.59  5433.9 1661.01
#Mann=8,-1,0
  3707.7    0.07       0  4371.4   0.035       0  4417.5    0.07       0
  4581.5   0.035       0  4866.5    0.07       0  4966.7    0.07       0
  4991.8    0.07       0  5423.7    0.16       0
Bank Sta=4966.7,4991.8
Exp/Cntr=0.3,0.1

Type RM Length L Ch R = 1,28698,1229,1229,1229
BEGIN DESCRIPTION:
Mapping XS 2ac0b0c6
END DESCRIPTION:
XS GIS Cut Line= 3
      1659754.43      6980450.09      1660657.19      6981344.17
      1661299.57      6981795.58
#Sta/Elev= 30
  3738.2 1706.72  3850.3 1704.64  3956.3 1695.26  4055.3 1676.76  4119.0 1661.60
  4217.9 1649.13  4239.2 1643.19  4324.0 1632.95  4380.6 1622.00  4610.9 1613.29
  4797.8 1606.42  4826.1 1607.95  4847.3 1606.05  4868.5 1608.61  4903.9 1609.06
  4937.3 1604.80  4941.9 1604.79  4967.5 1604.53  4968.8 1600.26  4969.3 1599.76
  4994.5 1600.26  5024.3 1607.10  5159.3 1608.97  5226.1 1609.85  5289.2 1620.78
  5390.2 1630.42  5491.3 1636.13  5669.9 1653.94  5771.0 1658.26  5793.9 1661.39
#Mann=7,-1,0
  3738.2    0.07       0  4610.9   0.035       0  4937.3    0.07       0
  4941.9   0.035       0  4968.8   0.035       0  4994.5   0.035       0
  5159.3    0.07       0
Bank Sta=4968.8,4994.5
Exp/Cntr=0.3,0.1

Type RM Length L Ch R = 1,27469,659,659,659
BEGIN DESCRIPTION:
Mapping XS e64d0469
END DESCRIPTION:
XS GIS Cut Line= 3
      1658929.77      6982044.04      1659802.16      6981944.22
      1661178.03      6981970.26
#Sta/Elev= 30
  4119.1 1699.78  4204.9 1694.00  4218.1 1690.87  4475.9 1662.96  4496.8 1659.11
  4537.0 1657.90  4647.8 1648.79  4678.0 1643.25  4798.7 1628.87  4939.7 1618.93
  4949.7 1617.48  4968.6 1607.68  4979.9 1602.22  5001.1 1597.98  5007.0 1593.25
  5007.5 1592.75  5033.1 1593.25  5070.0 1602.31  5090.0 1604.14  5235.7 1605.49
  5408.5 1605.44  5460.7 1605.64  5804.1 1607.58  5874.2 1609.53  5920.2 1612.17
  5960.2 1619.56  5987.5 1627.26  6180.2 1641.16  6240.2 1648.51  6373.3 1659.89
#Mann=9,-1,0
  4119.1    0.07       0  4968.6   0.035       0  5007.0   0.035       0
  5033.1   0.035       0  5235.7    0.07       0  5408.5   0.035       0
  5460.7    0.07       0  5804.1   0.035       0  5874.2    0.07       0
Bank Sta=5007,5033.1
Exp/Cntr=0.3,0.1

Type RM Length L Ch R = 1,26810,682,682,682
BEGIN DESCRIPTION:
Mapping XS 8ffa9926
END DESCRIPTION:
XS GIS Cut Line= 3
      1658986.20      6982690.74      1659858.58      6982586.58
      1661450.76      6982430.40
#Sta/Elev= 30
  4121.2 1701.80  4161.4 1699.87  4273.5 1688.80  4381.8 1675.33  4443.4 1673.02
  4492.6 1668.91  4565.8 1658.05  4573.1 1657.03  4608.3 1653.80  4673.9 1642.95
  4695.8 1641.39  4724.3 1634.52  4778.3 1628.18  4814.9 1618.15  4895.5 1603.00
  4966.0 1599.17  4993.1 1593.55  4993.6 1593.05  5019.3 1593.55  5033.9 1600.71
  5126.9 1600.82  5241.8 1601.80  5558.9 1599.64  5754.8 1601.31  6063.5 1612.00
  6322.5 1636.88  6423.0 1651.49  6474.4 1655.28  6569.6 1666.26  6599.6 1669.03
#Mann=9,-1,0
  4121.2   0.035       0  4161.4    0.07       0  4565.8    0.16       0
  4573.1    0.07       0  4993.1    0.07       0  5019.3    0.07       0
  5126.9   0.035       0  5754.8    0.07       0  6569.6    0.16       0
Bank Sta=4993.1,5019.3
Exp/Cntr=0.3,0.1

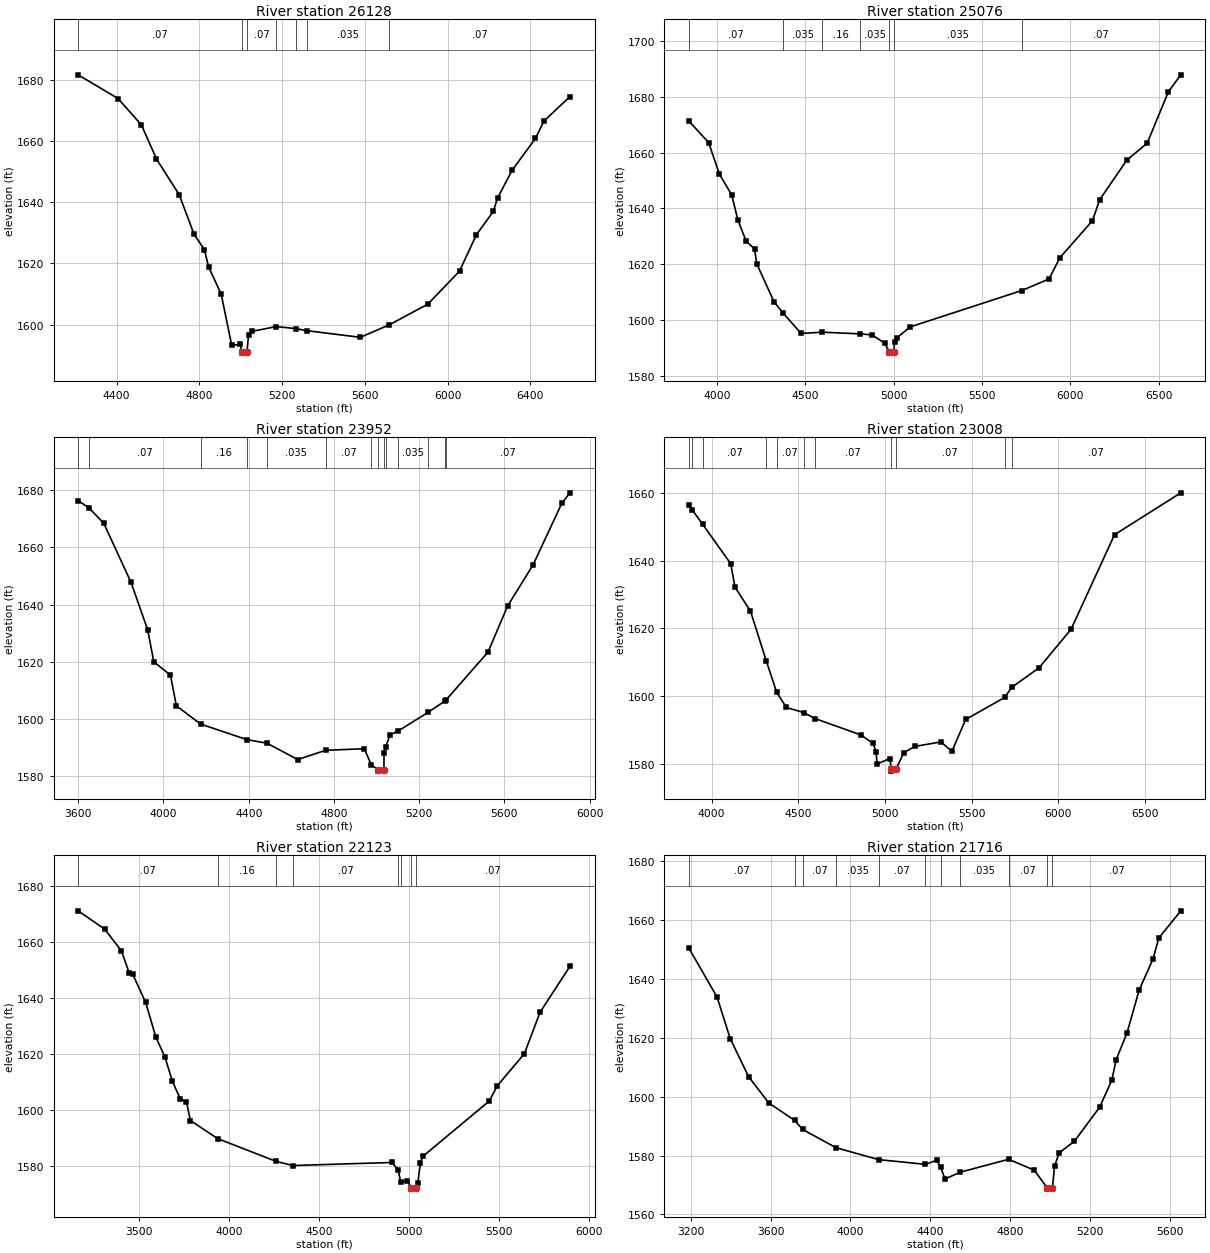
Type RM Length L Ch R = 1,26128,1052,1052,1052
BEGIN DESCRIPTION:
Mapping XS 1d5ca2a7
END DESCRIPTION:
XS GIS Cut Line= 3
      1659333.38      6983315.75      1660101.64      6983185.54
      1661668.47      6982873.04
#Sta/Elev= 30
  4214.5 1681.55  4407.1 1673.82  4520.4 1665.20  4593.2 1654.06  4703.0 1642.41
  4774.3 1629.55  4824.5 1624.48  4845.0 1618.84  4905.8 1609.95  4956.6 1593.26
  4998.0 1593.50  5004.4 1591.18  5004.9 1590.68  5030.6 1591.18  5037.9 1596.60
  5055.5 1597.80  5172.0 1599.34  5265.0 1598.70  5318.7 1598.02  5578.4 1595.84
  5718.5 1599.93  5904.7 1606.68  6057.6 1617.45  6139.2 1629.34  6220.8 1636.94
  6241.2 1641.30  6312.5 1650.46  6424.7 1660.80  6465.5 1666.44  6591.4 1674.46
#Mann=7,-1,0
  4214.5    0.07       0  5004.4    0.07       0  5030.6    0.07       0
  5172.0   0.035       0  5265.0    0.07       0  5318.7   0.035       0
  5718.5    0.07       0
Bank Sta=5004.4,5030.6
Exp/Cntr=0.3,0.1

Type RM Length L Ch R = 1,25076,1124,1124,1124
BEGIN DESCRIPTION:
Mapping XS 091bb92a
END DESCRIPTION:
XS GIS Cut Line= 3
      1659542.91      6983584.85      1660610.61      6984044.91
      1662193.77      6984383.23
#Sta/Elev= 30
  3842.6 1671.35  3953.8 1663.65  4014.2 1652.40  4084.4 1644.86  4119.2 1635.86
  4166.3 1628.21  4213.3 1625.51  4226.0 1620.11  4324.0 1606.46  4374.1 1602.54
  4476.4 1595.16  4597.6 1595.60  4810.7 1595.01  4879.4 1594.61  4950.0 1591.64
  4974.8 1588.60  4975.3 1588.10  5001.7 1588.60  5004.9 1592.02  5019.9 1593.70
  5094.2 1597.52  5723.2 1610.53  5878.9 1614.72  5940.2 1622.33  6124.3 1635.62
  6165.2 1643.13  6318.6 1657.35  6433.9 1663.45  6553.8 1681.90  6624.1 1687.96
#Mann=7,-1,0
  3842.6    0.07       0  4374.1   0.035       0  4597.6    0.16       0
  4810.7   0.035       0  4974.8   0.035       0  5001.7   0.035       0
  5723.2    0.07       0
Bank Sta=4974.8,5001.7
Exp/Cntr=0.3,0.1

Type RM Length L Ch R = 1,23952,944,944,944
BEGIN DESCRIPTION:
Mapping XS ad26e4d2
END DESCRIPTION:
XS GIS Cut Line= 3
      1659064.71      6983759.62      1659942.29      6984855.94
      1660569.90      6985506.99
#Sta/Elev= 30
  3599.4 1676.44  3650.9 1673.82  3719.4 1668.51  3847.5 1647.81  3925.9 1631.12
  3954.7 1619.93  4032.8 1615.28  4060.4 1604.53  4174.0 1598.13  4390.5 1592.70
  4486.7 1591.40  4630.2 1585.69  4760.6 1588.93  4942.4 1589.49  4975.9 1583.76
  5007.6 1582.14  5008.1 1581.64  5034.6 1582.14  5035.3 1587.85  5042.5 1590.04
  5063.6 1594.36  5100.2 1595.65  5242.0 1602.22  5322.7 1606.31  5325.5 1606.49
  5523.3 1623.35  5615.4 1639.51  5735.5 1654.01  5869.8 1675.50  5908.0 1679.14
#Mann=14,-1,0
  3599.4    0.16       0  3650.9    0.07       0  4174.0    0.16       0
  4390.5    0.07       0  4486.7   0.035       0  4760.6    0.07       0
  4975.9   0.035       0  5007.6   0.035       0  5034.6   0.035       0
  5042.5    0.07       0  5100.2   0.035       0  5242.0    0.07       0
  5322.7   0.035       0  5325.5    0.07       0
Bank Sta=5007.6,5034.6
Exp/Cntr=0.3,0.1

Type RM Length L Ch R = 1,23008,885,885,885
BEGIN DESCRIPTION:
Mapping XS 4e7c55a3
END DESCRIPTION:
XS GIS Cut Line= 3
      1658728.73      6983889.75      1659158.44      6984939.27
      1660528.21      6985949.67
#Sta/Elev= 30
  3870.1 1656.56  3887.6 1655.11  3949.5 1650.74  4111.2 1639.08  4135.2 1632.19
  4224.8 1625.09  4315.6 1610.43  4375.3 1601.15  4431.6 1596.63  4532.9 1595.09
  4596.3 1593.35  4862.3 1588.48  4930.9 1586.03  4948.8 1583.59  4954.9 1579.92
  5029.1 1581.53  5036.4 1578.30  5036.9 1577.80  5063.5 1578.30  5108.5 1583.27
  5173.3 1585.11  5323.0 1586.43  5386.2 1583.65  5465.6 1593.07  5690.2 1599.57
  5731.2 1602.58  5887.4 1608.26  6073.3 1619.71  6323.9 1647.69  6706.3 1660.07
#Mann=11,-1,0
  3870.1    0.07       0  3887.6    0.16       0  3949.5    0.07       0
  4315.6    0.16       0  4375.3    0.07       0  4532.9    0.16       0
  4596.3    0.07       0  5036.4    0.07       0  5063.5    0.07       0
  5690.2   0.035       0  5731.2    0.07       0
Bank Sta=5036.4,5063.5
Exp/Cntr=0.3,0.1

Type RM Length L Ch R = 1,22123,407,407,407
BEGIN DESCRIPTION:
Mapping XS 7c29602c
END DESCRIPTION:
XS GIS Cut Line= 3
      1657842.47      6984411.50      1659061.21      6985786.49
      1659550.40      6986532.42
#Sta/Elev= 30
  3163.4 1671.13  3311.4 1664.57  3403.4 1656.87  3446.1 1649.13  3467.0 1648.44
  3538.1 1638.47  3594.9 1626.07  3644.3 1619.19  3686.9 1610.29  3729.6 1604.20
  3764.7 1602.93  3786.5 1596.38  3937.1 1589.94  4259.2 1581.88  4354.1 1580.33
  4905.5 1581.42  4938.2 1578.82  4953.9 1574.60  4990.0 1574.76  5012.8 1572.42
  5013.3 1571.92  5040.2 1572.42  5048.8 1574.25  5062.4 1581.16  5075.9 1583.57
  5445.0 1603.33  5488.9 1608.71  5639.6 1620.19  5727.0 1635.00  5892.8 1651.36
#Mann=8,-1,0
  3163.4    0.07       0  3937.1    0.16       0  4259.2   0.035       0
  4354.1    0.07       0  4938.2   0.035       0  4953.9    0.07       0
  5012.8    0.07       0  5040.2    0.07       0
Bank Sta=5012.8,5040.2
Exp/Cntr=0.3,0.1

Type RM Length L Ch R = 1,21716,375,375,375
BEGIN DESCRIPTION:
Mapping XS 9d14c9f2
END DESCRIPTION:
XS GIS Cut Line= 3
      1657351.16      6985074.70      1658840.73      6986105.94
      1659103.81      6986704.80
#Sta/Elev= 30
  3190.6 1650.44  3331.6 1633.83  3397.2 1619.77  3489.8 1606.78  3591.1 1597.86
  3720.9 1591.94  3760.4 1588.88  3928.7 1582.66  4143.1 1578.62  4375.3 1577.04
  4432.4 1578.38  4451.9 1576.12  4474.3 1572.04  4548.5 1574.33  4792.8 1578.74
  4921.6 1575.06  4985.6 1569.11  4986.1 1568.61  5013.0 1569.11  5023.1 1576.35
  5046.5 1580.94  5122.0 1584.82  5249.7 1596.47  5310.4 1605.63  5332.2 1612.58
  5386.8 1621.71  5447.5 1636.26  5517.5 1646.89  5546.3 1653.98  5656.4 1663.17
#Mann=11,-1,0
  3190.6    0.07       0  3720.9   0.035       0  3760.4    0.07       0
  3928.7   0.035       0  4143.1    0.07       0  4375.3   0.035       0
  4451.9    0.07       0  4548.5   0.035       0  4792.8    0.07       0
  4985.6    0.07       0  5013.0    0.07       0
Bank Sta=4985.6,5013
Exp/Cntr=0.3,0.1

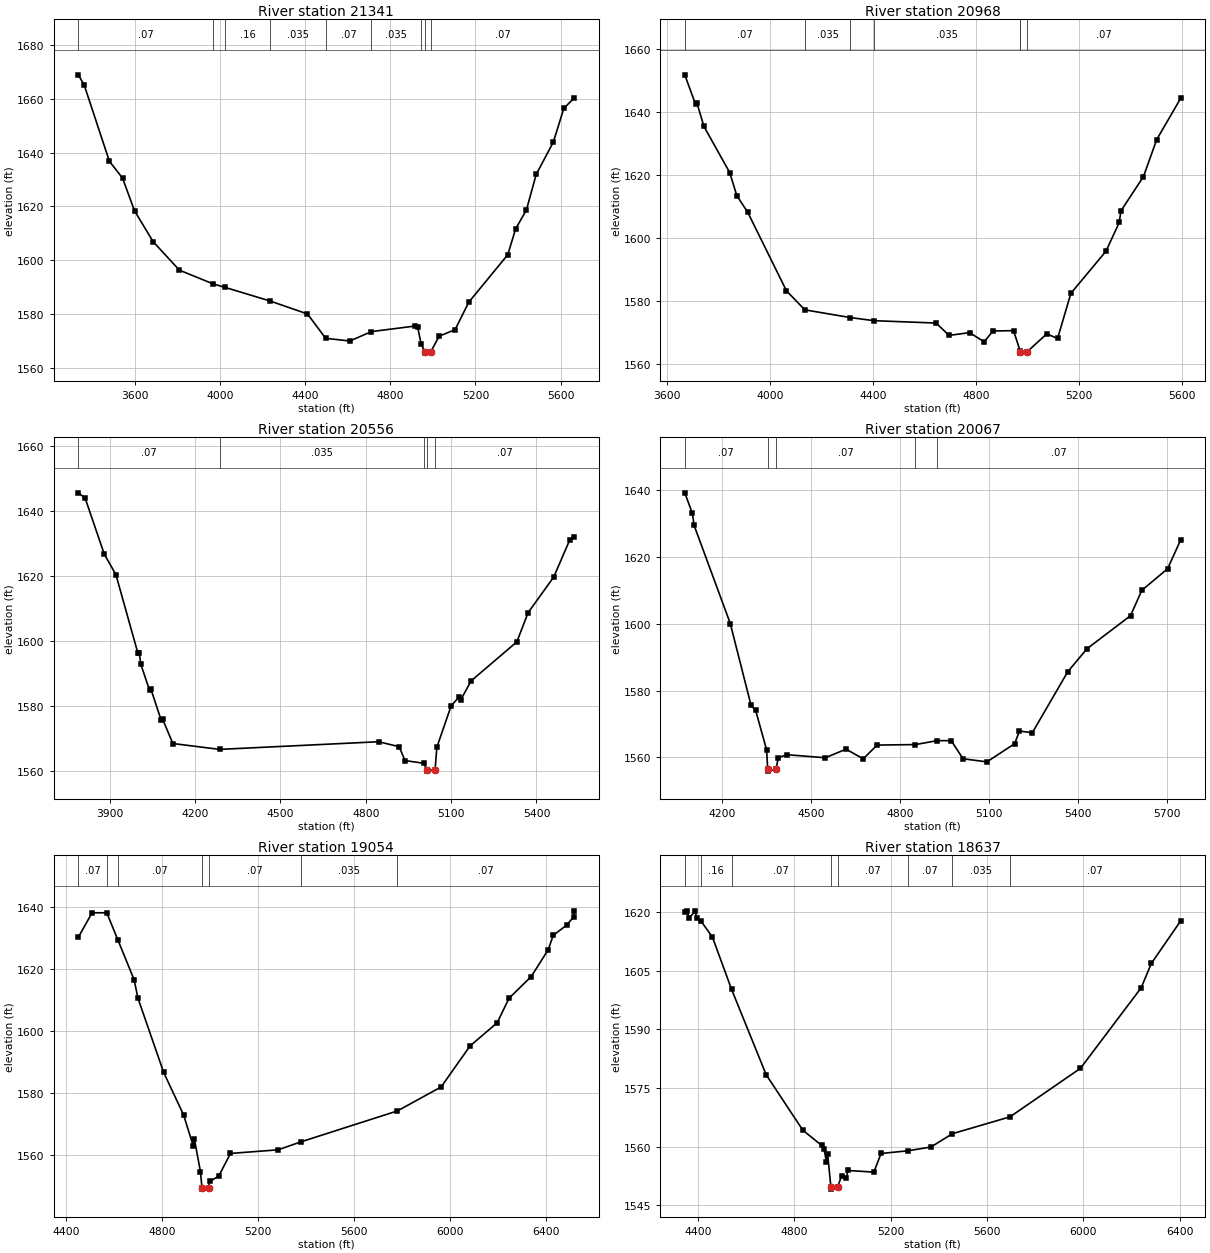
Type RM Length L Ch R = 1,21341,373,373,373
BEGIN DESCRIPTION:
Mapping XS 131c119b
END DESCRIPTION:
XS GIS Cut Line= 3
      1656952.72      6985714.25      1658529.15      6986273.30
      1658855.55      6986842.76
#Sta/Elev= 30
  3334.7 1668.88  3362.3 1665.08  3480.5 1636.79  3542.2 1630.55  3598.6 1618.39
  3686.0 1606.91  3809.5 1596.33  3967.8 1591.22  4025.6 1589.89  4233.7 1584.91
  4411.1 1580.06  4496.6 1571.00  4610.3 1570.02  4711.5 1573.51  4914.7 1575.55
  4928.6 1575.21  4945.2 1568.80  4962.8 1566.01  4963.3 1565.51  4990.2 1566.01
  5029.6 1571.80  5104.4 1574.24  5169.1 1584.47  5351.8 1602.05  5389.2 1611.75
  5439.2 1618.62  5485.3 1631.86  5566.0 1643.92  5615.1 1656.43  5663.7 1660.28
#Mann=9,-1,0
  3334.7    0.07       0  3967.8   0.035       0  4025.6    0.16       0
  4233.7   0.035       0  4496.6    0.07       0  4711.5   0.035       0
  4945.2    0.07       0  4962.8    0.07       0  4990.2    0.07       0
Bank Sta=4962.8,4990.2
Exp/Cntr=0.3,0.1

Type RM Length L Ch R = 1,20968,412,412,412
BEGIN DESCRIPTION:
Mapping XS ac9e1f67
END DESCRIPTION:
XS GIS Cut Line= 3
      1656911.09      6986585.80      1658240.96      6986502.46
      1658740.45      6986821.58
#Sta/Elev= 30
  3668.0 1651.67  3709.9 1642.28  3714.9 1642.82  3742.1 1635.38  3842.3 1620.73
  3870.0 1613.44  3912.4 1608.16  4062.7 1583.31  4134.0 1577.29  4310.3 1574.85
  4402.0 1573.86  4643.8 1573.11  4693.9 1569.20  4774.1 1570.08  4830.6 1567.16
  4864.3 1570.59  4944.4 1570.71  4970.5 1564.18  4970.8 1564.09  4971.3 1563.59
  4998.2 1564.09  5073.2 1569.67  5115.5 1568.24  5167.1 1582.52  5303.3 1595.84
  5354.9 1604.95  5361.3 1608.60  5448.8 1619.45  5500.4 1631.19  5593.2 1644.21
#Mann=7,-1,0
  3668.0    0.07       0  4134.0   0.035       0  4310.3    0.07       0
  4402.0   0.035       0  4970.5    0.07       0  4970.8    0.07       0
  4998.2    0.07       0
Bank Sta=4970.8,4998.2
Exp/Cntr=0.3,0.1

Type RM Length L Ch R = 1,20556,489,489,489
BEGIN DESCRIPTION:
Mapping XS 53c85db7
END DESCRIPTION:
XS GIS Cut Line= 3
      1656931.89      6987155.25      1658102.07      6986860.10
      1658636.82      6986832.32
#Sta/Elev= 30
  3790.2 1645.54  3814.0 1643.94  3881.1 1626.77  3922.2 1620.41  3999.2 1596.38
  4004.3 1596.29  4010.0 1592.80  4040.3 1584.92  4045.4 1585.19  4081.3 1575.69
  4086.5 1575.97  4122.4 1568.52  4286.9 1566.72  4845.4 1569.07  4917.5 1567.55
  4938.2 1563.28  5003.1 1562.46  5016.2 1560.54  5016.7 1560.04  5043.9 1560.54
  5050.0 1567.37  5100.1 1580.07  5129.5 1582.96  5134.5 1582.00  5170.2 1587.75
  5331.1 1599.75  5370.5 1608.70  5460.6 1619.66  5517.6 1631.18  5532.5 1631.97
#Mann=5,-1,0
  3790.2    0.07       0  4286.9   0.035       0  5003.1    0.07       0
  5016.2   0.035       0  5043.9    0.07       0
Bank Sta=5016.2,5043.9
Exp/Cntr=0.3,0.1

Type RM Length L Ch R = 1,20067,1013,1013,1013
BEGIN DESCRIPTION:
Mapping XS fc1d1626
END DESCRIPTION:
XS GIS Cut Line= 3
      1657066.33      6987653.15      1657913.53      6987281.63
      1658566.32      6986920.51
#Sta/Elev= 30
  4075.7 1639.15  4101.3 1633.00  4107.0 1629.43  4229.0 1600.07  4299.1 1575.55
  4314.5 1574.08  4351.3 1562.33  4355.2 1556.42  4355.7 1555.92  4382.9 1556.42
  4390.9 1559.98  4421.4 1560.82  4549.2 1559.92  4619.3 1562.49  4677.0 1559.58
  4723.7 1563.71  4853.2 1563.86  4926.1 1565.04  4973.8 1565.02  5013.4 1559.62
  5093.9 1558.69  5187.5 1564.13  5203.5 1567.90  5247.0 1567.41  5366.1 1585.60
  5431.4 1592.54  5578.0 1602.41  5615.8 1609.97  5702.8 1616.44  5746.8 1625.03
#Mann=5,-1,0
  4075.7    0.07       0  4355.2    0.07       0  4382.9    0.07       0
  4853.2   0.035       0  4926.1    0.07       0
Bank Sta=4355.2,4382.9
Exp/Cntr=0.3,0.1

Type RM Length L Ch R = 1,19054,417,417,417
BEGIN DESCRIPTION:
Swager Creek 33.0
END DESCRIPTION:
XS GIS Cut Line= 3
      1657058.02      6987984.54      1657605.08      6988028.21
      1658650.50      6986930.32
#Sta/Elev= 30
  4451.2 1630.28  4508.4 1638.19  4569.7 1638.17  4615.7 1629.45  4683.6 1616.58
  4699.0 1610.75  4806.6 1586.69  4889.6 1572.99  4929.6 1563.01  4934.6 1565.16
  4959.8 1554.67  4966.0 1549.57  4966.5 1549.07  4993.8 1549.57  4997.5 1551.54
  5035.5 1553.22  5084.8 1560.58  5283.0 1561.74  5377.9 1564.31  5780.0 1574.29
  5962.1 1582.02  6082.2 1595.22  6195.5 1602.73  6244.8 1610.62  6337.0 1617.60
  6407.8 1626.24  6428.9 1630.91  6485.5 1634.23  6513.8 1636.86  6516.0 1638.81
#Mann=7,-1,0
  4451.2    0.07       0  4569.7    0.16       0  4615.7    0.07       0
  4966.0    0.07       0  4993.8    0.07       0  5377.9   0.035       0
  5780.0    0.07       0
Bank Sta=4966,4993.8
Exp/Cntr=0.3,0.1

Type RM Length L Ch R = 1,18637,1177,1177,1177
BEGIN DESCRIPTION:
Swager Creek 32.0
END DESCRIPTION:
XS GIS Cut Line= 3
      1657161.80      6988178.99      1657787.86      6988371.53
      1658570.31      6987205.53
#Sta/Elev= 30
  4345.0 1620.04  4356.1 1620.39  4361.3 1618.54  4388.8 1620.25  4394.1 1618.45
  4412.1 1617.76  4459.5 1613.69  4539.3 1600.26  4683.1 1578.38  4834.9 1564.20
  4913.3 1560.28  4923.8 1559.25  4933.0 1556.11  4938.2 1558.14  4951.7 1549.58
  4952.2 1549.08  4979.5 1549.58  4995.9 1552.42  5016.0 1551.84  5022.1 1553.86
  5130.1 1553.44  5160.1 1558.21  5271.0 1558.90  5367.2 1559.87  5456.4 1563.28
  5695.5 1567.60  5988.3 1580.04  6240.4 1600.67  6282.4 1606.90  6404.2 1617.79
#Mann=8,-1,0
  4345.0    0.07       0  4412.1    0.16       0  4539.3    0.07       0
  4951.7   0.035       0  4979.5    0.07       0  5271.0    0.07       0
  5456.4   0.035       0  5695.5    0.07       0
Bank Sta=4951.7,4979.5
Exp/Cntr=0.3,0.1

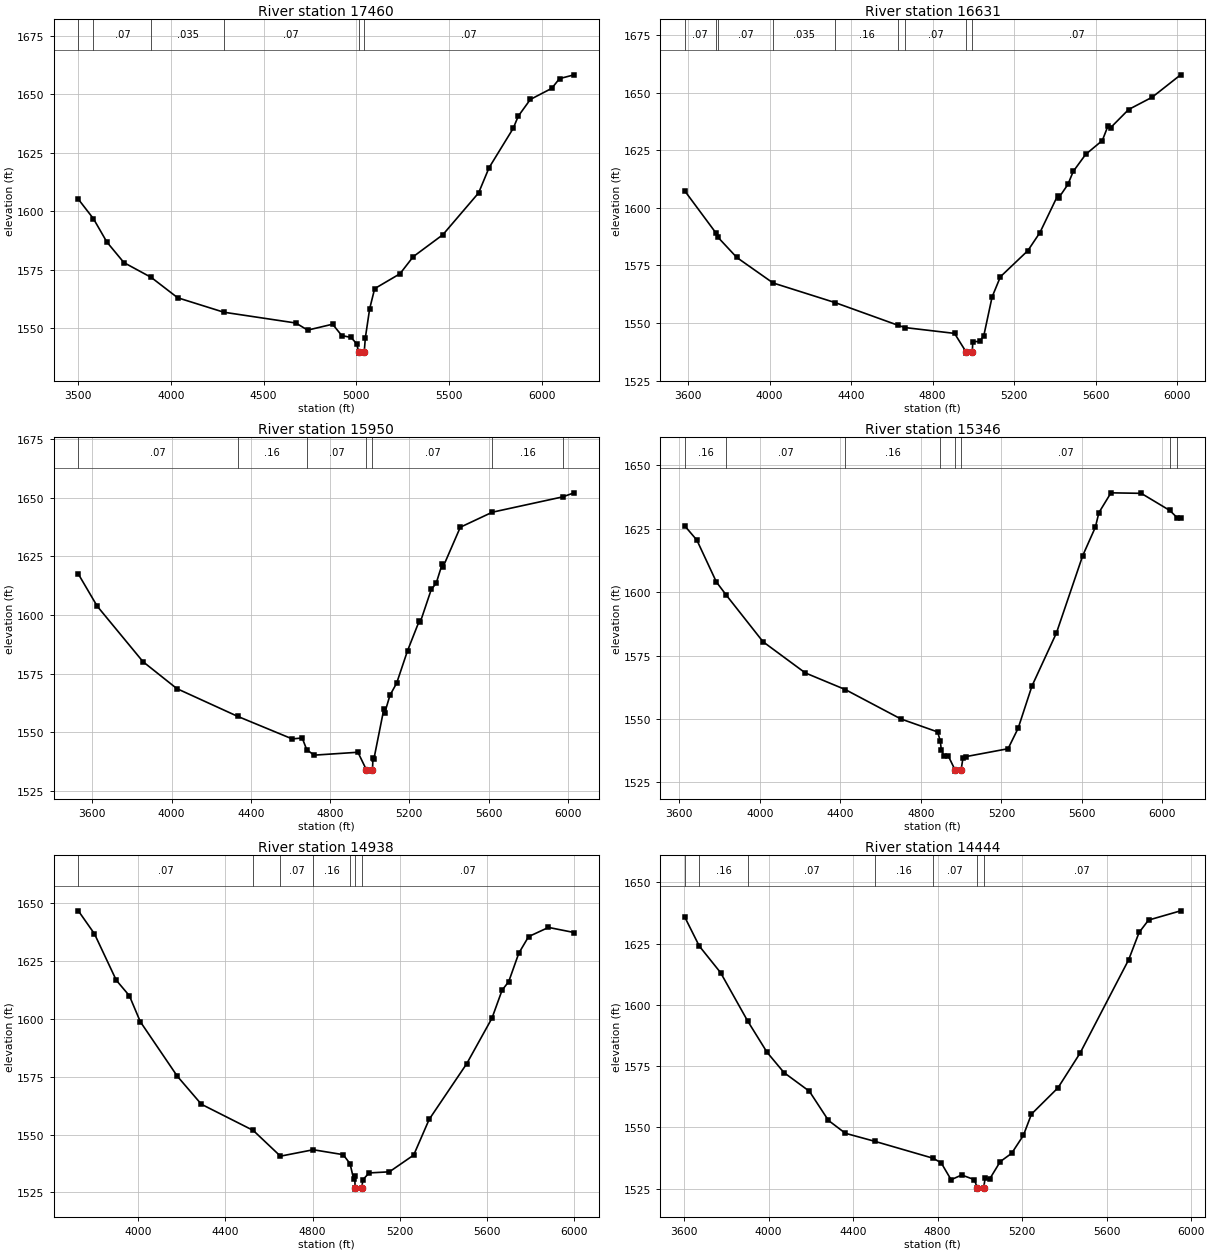
Type RM Length L Ch R = 1,17460,829,829,829
BEGIN DESCRIPTION:
Swager Creek 30.0
END DESCRIPTION:
XS GIS Cut Line= 3
      1657211.96      6988263.94      1658225.46      6989368.26
      1658908.08      6990324.27
#Sta/Elev= 30
  3501.1 1605.17  3582.6 1596.84  3655.0 1586.87  3746.9 1578.08  3894.3 1571.75
  4036.7 1563.06  4285.6 1556.88  4673.9 1552.27  4737.7 1549.23  4872.2 1551.76
  4921.5 1546.91  4971.4 1546.10  5002.9 1543.35  5012.7 1539.90  5013.2 1539.40
  5042.7 1539.90  5048.8 1545.98  5072.0 1558.35  5099.0 1566.96  5235.4 1573.31
  5306.9 1580.61  5466.5 1589.98  5659.4 1607.86  5715.9 1618.64  5846.2 1635.47
  5873.2 1640.65  5938.4 1647.80  6053.9 1652.55  6095.7 1656.70  6174.7 1658.32
#Mann=6,-1,0
  3501.1    0.16       0  3582.6    0.07       0  3894.3   0.035       0
  4285.6    0.07       0  5012.7    0.07       0  5042.7    0.07       0
Bank Sta=5012.7,5042.7
Exp/Cntr=0.3,0.1

Type RM Length L Ch R = 1,16631,681,681,681
BEGIN DESCRIPTION:
Mapping XS 9c611705
END DESCRIPTION:
XS GIS Cut Line= 3
      1657107.79      6988229.20      1657507.11      6989587.74
      1657710.80      6990584.53
#Sta/Elev= 30
  3583.8 1607.40  3735.0 1589.33  3745.5 1587.37  3838.9 1578.49  4016.8 1567.41
  4323.1 1558.82  4631.5 1548.97  4664.5 1548.01  4907.6 1545.48  4964.4 1537.40
  4964.9 1536.90  4994.6 1537.40  4997.3 1541.89  5030.7 1541.97  5051.1 1544.43
  5091.9 1561.31  5132.8 1570.11  5267.3 1581.44  5326.7 1589.31  5413.6 1605.36
  5418.7 1604.37  5464.1 1610.25  5490.0 1615.87  5551.2 1623.30  5632.9 1629.33
  5661.0 1635.74  5673.7 1634.92  5762.0 1642.81  5877.8 1648.17  6017.2 1657.89
#Mann=9,-1,0
  3583.8    0.07       0  3735.0    0.16       0  3745.5    0.07       0
  4016.8   0.035       0  4323.1    0.16       0  4631.5   0.035       0
  4664.5    0.07       0  4964.4    0.07       0  4994.6    0.07       0
Bank Sta=4964.4,4994.6
Exp/Cntr=0.3,0.1

Type RM Length L Ch R = 1,15950,604,604,604
BEGIN DESCRIPTION:
Mapping XS d5a9ddd0
END DESCRIPTION:
XS GIS Cut Line= 3
      1657007.97      6988072.99      1656869.09      6989548.67
      1657042.48      6990554.34
#Sta/Elev= 30
  3529.2 1617.43  3624.6 1603.70  3855.6 1580.05  4026.4 1568.58  4332.9 1556.76
  4609.0 1547.12  4659.2 1547.53  4682.1 1542.53  4719.4 1540.20  4940.4 1541.44
  4983.6 1533.89  4984.1 1533.39  5013.8 1533.89  5016.3 1538.79  5021.4 1538.70
  5071.1 1559.76  5076.2 1558.35  5102.0 1565.70  5136.0 1570.92  5190.8 1584.71
  5250.7 1597.58  5255.8 1597.05  5310.6 1610.84  5335.4 1613.48  5365.4 1621.57
  5370.4 1620.48  5457.2 1637.38  5618.5 1643.78  5973.2 1650.31  6031.9 1652.05
#Mann=7,-1,0
  3529.2    0.07       0  4332.9    0.16       0  4682.1    0.07       0
  4983.6    0.07       0  5013.8    0.07       0  5618.5    0.16       0
  5973.2   0.035       0
Bank Sta=4983.6,5013.8
Exp/Cntr=0.3,0.1

Type RM Length L Ch R = 1,15346,408,408,408
BEGIN DESCRIPTION:
Mapping XS 9ec29069
END DESCRIPTION:
XS GIS Cut Line= 3
      1656964.58      6987912.37      1656448.08      6989201.45
      1656517.51      6990273.30
#Sta/Elev= 30
  3627.5 1626.12  3687.4 1620.55  3784.4 1604.03  3834.2 1598.78  4016.1 1580.46
  4226.0 1568.17  4424.9 1561.60  4700.1 1550.04  4883.2 1544.90  4896.7 1541.32
  4901.4 1537.83  4915.5 1535.37  4937.1 1535.28  4969.7 1529.94  4970.2 1529.44
  5000.0 1529.94  5009.1 1534.58  5022.8 1535.15  5233.2 1538.28  5283.3 1546.36
  5351.9 1563.01  5473.7 1583.98  5604.0 1614.42  5666.9 1625.65  5684.2 1631.35
  5744.3 1639.19  5894.6 1638.99  6036.6 1632.23  6074.6 1629.27  6090.3 1629.31
#Mann=8,-1,0
  3627.5    0.16       0  3834.2    0.07       0  4424.9    0.16       0
  4896.7    0.07       0  4969.7    0.07       0  5000.0    0.07       0
  6036.6    0.16       0  6074.6    0.07       0
Bank Sta=4969.7,5000
Exp/Cntr=0.3,0.1

Type RM Length L Ch R = 1,14938,494,494,494
BEGIN DESCRIPTION:
Mapping XS 97ad8d01
END DESCRIPTION:
XS GIS Cut Line= 3
      1656045.59      6987814.06      1656080.31      6989090.05
      1656240.72      6990074.20
#Sta/Elev= 30
  3725.8 1646.57  3799.8 1636.63  3899.8 1616.61  3959.8 1609.92  4009.9 1598.72
  4179.9 1575.15  4290.0 1563.08  4527.9 1551.77  4652.5 1540.67  4803.0 1543.44
  4940.2 1541.32  4971.7 1537.43  4988.0 1530.85  4993.0 1532.18  4995.2 1526.94
  4995.7 1526.44  5025.5 1526.94  5030.6 1530.50  5059.2 1533.43  5152.2 1533.91
  5263.6 1541.14  5334.5 1556.54  5506.8 1580.59  5622.6 1600.25  5668.9 1612.31
  5699.3 1616.01  5745.6 1628.29  5790.5 1635.44  5881.7 1639.41  5999.4 1637.20
#Mann=7,-1,0
  3725.8    0.07       0  4527.9    0.16       0  4652.5    0.07       0
  4803.0    0.16       0  4971.7    0.07       0  4995.2    0.07       0
  5025.5    0.07       0
Bank Sta=4995.2,5025.5
Exp/Cntr=0.3,0.1

Type RM Length L Ch R = 1,14444,600,600,600
BEGIN DESCRIPTION:
Mapping XS 88514e92
END DESCRIPTION:
XS GIS Cut Line= 3
      1655654.96      6987748.95      1655602.88      6989150.82
      1655876.23      6990053.30
#Sta/Elev= 30
  3604.0 1635.85  3672.4 1624.05  3773.2 1613.19  3901.7 1593.39  3993.3 1580.64
  4073.4 1572.36  4193.5 1564.74  4283.5 1552.85  4363.6 1547.59  4504.1 1544.28
  4778.8 1537.40  4817.0 1535.52  4863.9 1528.62  4913.9 1530.56  4974.0 1528.66
  4987.7 1525.29  4988.2 1524.79  5018.1 1525.29  5024.8 1529.24  5045.7 1528.83
  5096.5 1536.03  5150.2 1539.40  5205.8 1546.72  5244.2 1555.43  5369.6 1566.16
  5474.1 1580.32  5703.9 1618.44  5753.4 1629.60  5798.0 1634.64  5949.8 1638.42
#Mann=7,-1,0
  3604.0    0.07       0  3672.4    0.16       0  3901.7    0.07       0
  4504.1    0.16       0  4778.8    0.07       0  4987.7    0.07       0
  5018.1    0.07       0
Bank Sta=4987.7,5018.1
Exp/Cntr=0.3,0.1