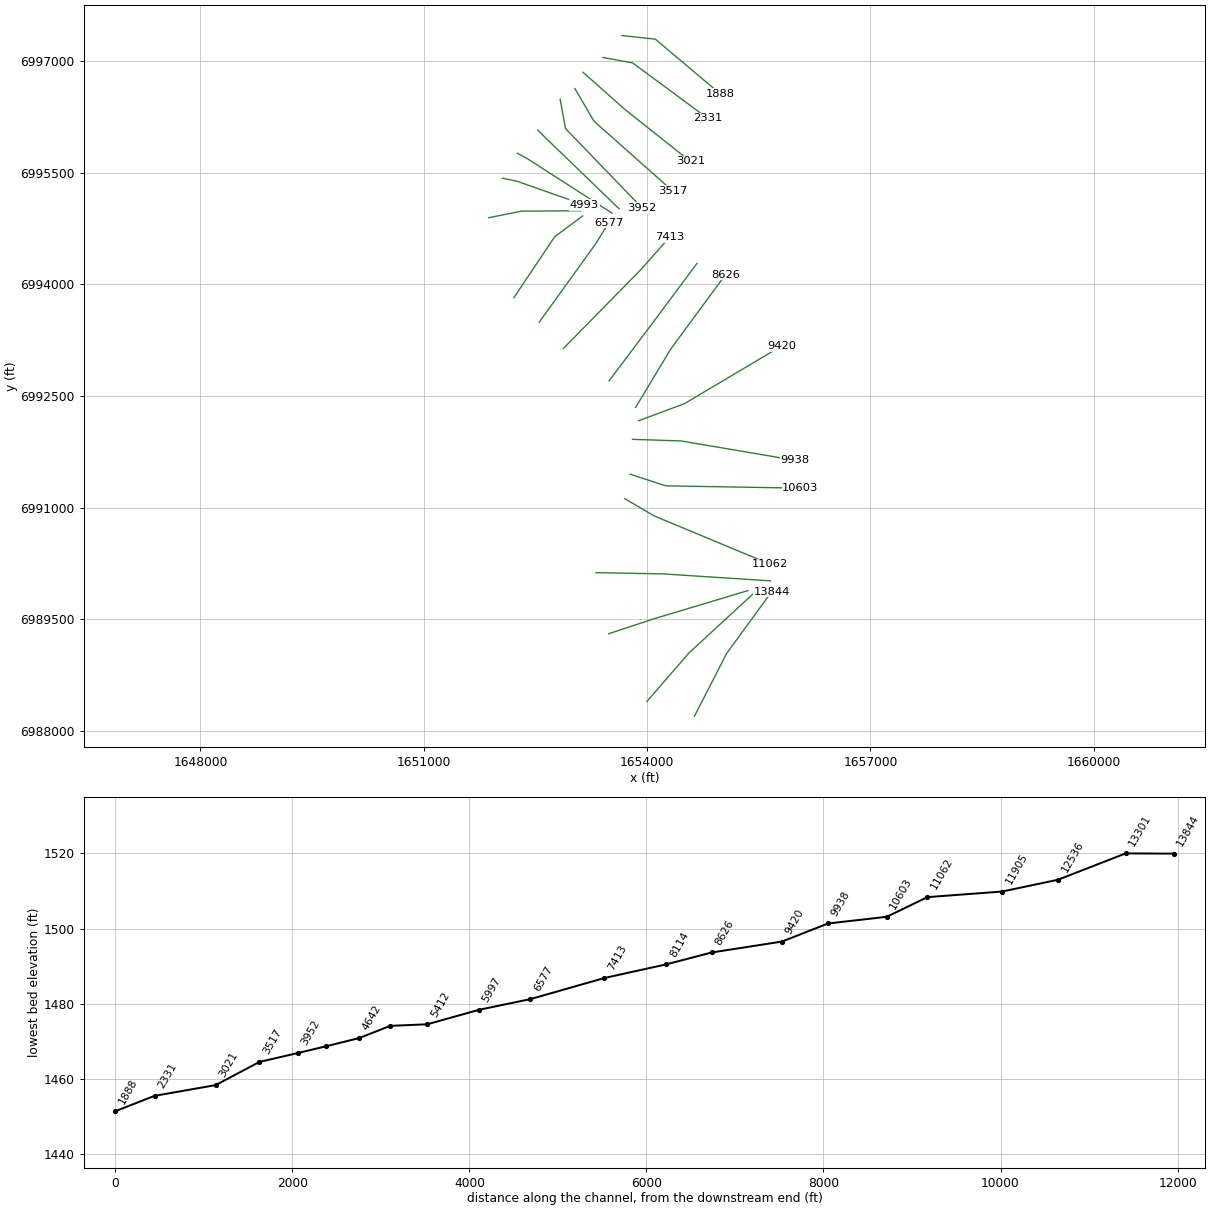
HEC-RAS study Swager Creek.prj: Swager Creek Base Level Engineering

--- Swager Creek.g01 (geometry) --- (continued)

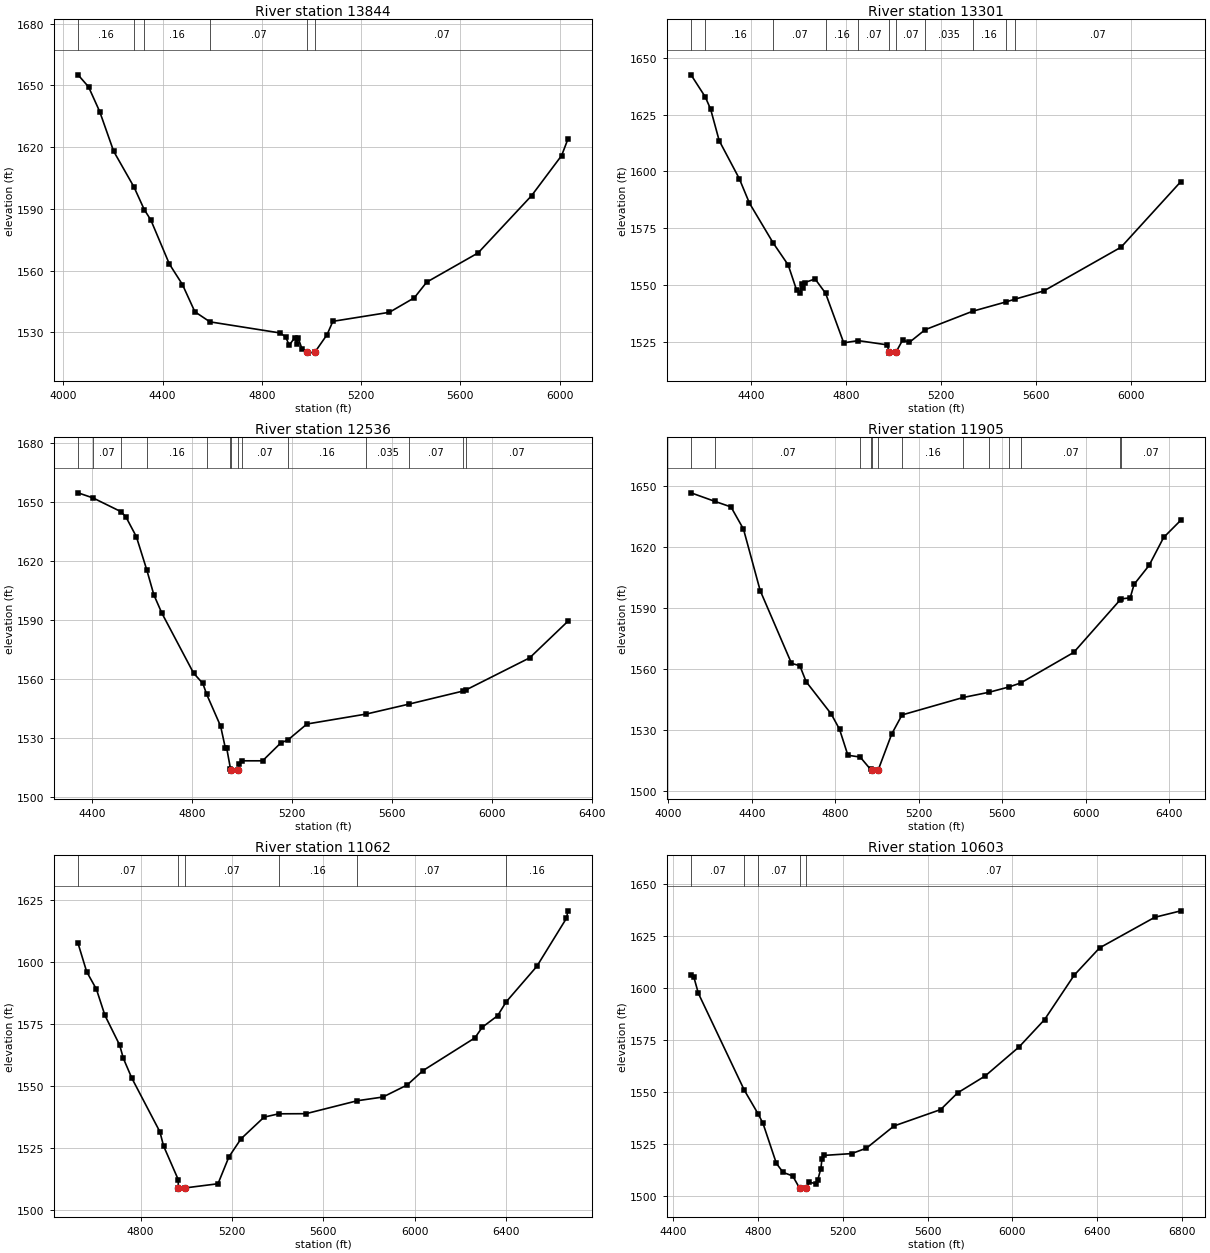
Type RM Length L Ch R = 1,13844,543,543,543
BEGIN DESCRIPTION:
Mapping XS 834f6894
END DESCRIPTION:
XS GIS Cut Line= 3
      1654637.07      6988200.27      1655067.64      6989040.57
      1655674.97      6989873.48
#Sta/Elev= 30
  4058.8 1655.17  4101.2 1649.32  4146.1 1637.32  4202.4 1618.03  4284.6 1600.60
  4325.7 1589.69  4352.2 1584.64  4427.0 1563.24  4479.7 1553.26  4529.8 1540.03
  4590.5 1535.13  4873.7 1529.73  4895.9 1527.81  4910.2 1523.75  4932.7 1527.51
  4940.3 1524.49  4946.0 1527.39  4962.5 1521.71  4983.5 1520.43  4984.0 1519.93
  5013.9 1520.43  5062.9 1528.94  5086.1 1535.38  5314.0 1539.77  5414.4 1546.81
  5464.6 1554.44  5671.6 1568.62  5887.1 1596.43  6008.4 1615.94  6033.8 1623.97
#Mann=6,-1,0
  4058.8    0.16       0  4284.6    0.07       0  4325.7    0.16       0
  4590.5    0.07       0  4983.5    0.07       0  5013.9    0.07       0
Bank Sta=4983.5,5013.9
Exp/Cntr=0.3,0.1

Type RM Length L Ch R = 1,13301,765,765,765
BEGIN DESCRIPTION:
Mapping XS bade8c46
END DESCRIPTION:
XS GIS Cut Line= 3
      1653998.16      6988398.17      1654560.70      6989047.52
      1655445.83      6989863.23
#Sta/Elev= 30
  4148.0 1642.52  4208.0 1632.78  4230.5 1627.40  4266.6 1613.53  4351.1 1596.84
  4393.8 1586.06  4493.9 1568.49  4557.2 1558.79  4592.3 1547.80  4606.6 1546.39
  4613.2 1550.30  4620.9 1548.47  4627.5 1551.07  4670.2 1552.66  4714.4 1546.38
  4790.9 1524.53  4852.3 1525.50  4975.1 1523.61  4980.6 1520.49  4981.1 1519.99
  5011.3 1520.49  5039.0 1525.72  5067.4 1524.73  5133.6 1530.29  5333.8 1538.43
  5472.4 1542.48  5513.3 1543.79  5633.3 1547.36  5958.9 1566.65  6210.8 1595.54
#Mann=11,-1,0
  4148.0    0.07       0  4208.0    0.16       0  4493.9    0.07       0
  4714.4    0.16       0  4852.3    0.07       0  4980.6    0.07       0
  5011.3    0.07       0  5133.6   0.035       0  5333.8    0.16       0
  5472.4   0.035       0  5513.3    0.07       0
Bank Sta=4980.6,5011.3
Exp/Cntr=0.3,0.1

Type RM Length L Ch R = 1,12536,631,631,631
BEGIN DESCRIPTION:
Mapping XS 8ffe7054
END DESCRIPTION:
XS GIS Cut Line= 3
      1653483.29      6989307.60      1654104.79      6989512.45
      1655354.77      6989887.44
#Sta/Elev= 30
  4345.4 1654.64  4404.8 1652.07  4516.9 1645.07  4536.7 1642.43  4578.8 1632.28
  4620.2 1615.47  4648.7 1602.70  4680.5 1593.44  4807.6 1562.86  4844.6 1557.61
  4860.0 1552.05  4915.8 1535.82  4934.6 1524.74  4939.9 1524.77  4955.1 1514.21
  4956.2 1513.48  4956.7 1512.98  4987.0 1513.48  4989.5 1516.41  5003.0 1518.23
  5083.5 1518.23  5156.6 1527.37  5184.9 1528.84  5261.0 1536.97  5498.4 1542.04
  5669.9 1547.12  5885.9 1553.76  5896.4 1554.27  6151.9 1570.65  6304.8 1589.27
#Mann=14,-1,0
  4345.4   0.035       0  4404.8    0.07       0  4516.9   0.035       0
  4620.2    0.16       0  4860.0    0.07       0  4955.1    0.16       0
  4956.2    0.07       0  4987.0    0.16       0  5003.0    0.07       0
  5184.9    0.16       0  5498.4   0.035       0  5669.9    0.07       0
  5885.9   0.035       0  5896.4    0.07       0
Bank Sta=4956.2,4987
Exp/Cntr=0.3,0.1

Type RM Length L Ch R = 1,11905,843,843,843
BEGIN DESCRIPTION:
Mapping XS fd2d1243
END DESCRIPTION:
XS GIS Cut Line= 3
      1653313.76      6990128.21      1654199.20      6990112.59
      1655657.51      6990018.84
#Sta/Elev= 30
  4108.2 1646.53  4221.2 1642.38  4299.5 1639.61  4359.5 1628.70  4439.5 1598.51
  4589.5 1562.78  4629.5 1561.62  4659.5 1553.79  4779.5 1537.96  4819.6 1530.42
  4859.6 1517.65  4918.5 1516.76  4968.1 1510.73  4973.8 1510.35  4974.3 1509.85
  5004.6 1510.35  5069.7 1528.10  5118.9 1537.44  5411.9 1546.02  5535.9 1548.58
  5631.4 1551.19  5687.5 1553.14  5941.5 1568.15  6163.8 1593.93  6168.1 1594.43
  6212.1 1594.96  6230.7 1601.58  6302.3 1610.84  6372.4 1624.62  6455.1 1633.13
#Mann=13,-1,0
  4108.2   0.035       0  4221.2    0.07       0  4918.5   0.035       0
  4968.1    0.07       0  4973.8    0.07       0  5004.6    0.07       0
  5118.9    0.16       0  5411.9   0.035       0  5535.9    0.07       0
  5631.4   0.035       0  5687.5    0.07       0  6163.8    0.16       0
  6168.1    0.07       0
Bank Sta=4973.8,5004.6
Exp/Cntr=0.3,0.1

Type RM Length L Ch R = 1,11062,459,459,459
BEGIN DESCRIPTION:
Mapping XS 07375ee8
END DESCRIPTION:
XS GIS Cut Line= 3
      1653699.19      6991123.01      1654100.24      6990888.63
      1655650.94      6990243.37
#Sta/Elev= 30
  4526.6 1607.60  4564.3 1596.15  4607.2 1589.03  4644.4 1578.49  4708.9 1566.50
  4724.6 1561.24  4761.8 1553.21  4885.0 1531.49  4900.7 1525.85  4965.1 1512.22
  4965.4 1508.87  4965.9 1508.37  4996.3 1508.87  5139.2 1510.54  5186.9 1521.38
  5240.0 1528.69  5340.8 1537.43  5405.0 1538.77  5524.0 1538.82  5749.4 1544.06
  5861.0 1545.55  5967.3 1550.42  6036.1 1556.20  6263.5 1569.42  6296.0 1573.73
  6362.9 1578.37  6400.6 1583.98  6534.3 1598.26  6664.3 1617.71  6670.7 1620.71
#Mann=6,-1,0
  4526.6    0.07       0  4965.4    0.07       0  4996.3    0.07       0
  5405.0    0.16       0  5749.4    0.07       0  6400.6    0.16       0
Bank Sta=4965.4,4996.3
Exp/Cntr=0.3,0.1

Type RM Length L Ch R = 1,10603,665,665,665
BEGIN DESCRIPTION:
Mapping XS e98ec9e4
END DESCRIPTION:
XS GIS Cut Line= 3
      1653772.14      6991451.12      1654251.28      6991294.88
      1656058.53      6991263.63
#Sta/Elev= 30
  4483.7 1606.49  4497.2 1605.17  4518.3 1597.43  4735.0 1550.81  4801.1 1539.22
  4823.3 1534.79  4886.4 1515.54  4918.0 1511.21  4963.4 1509.48  4995.8 1503.64
  4996.3 1503.14  5026.9 1503.64  5041.4 1506.48  5071.4 1505.80  5081.4 1507.44
  5096.3 1513.02  5101.4 1517.51  5111.4 1519.38  5241.4 1520.25  5311.4 1522.87
  5441.5 1533.56  5661.5 1541.45  5741.5 1549.49  5871.5 1557.63  6031.6 1571.62
  6151.6 1584.75  6291.6 1606.18  6411.6 1619.33  6671.6 1634.04  6795.2 1637.16
#Mann=5,-1,0
  4483.7    0.07       0  4735.0   0.035       0  4801.1    0.07       0
  4995.8    0.07       0  5026.9    0.07       0
Bank Sta=4995.8,5026.9
Exp/Cntr=0.3,0.1

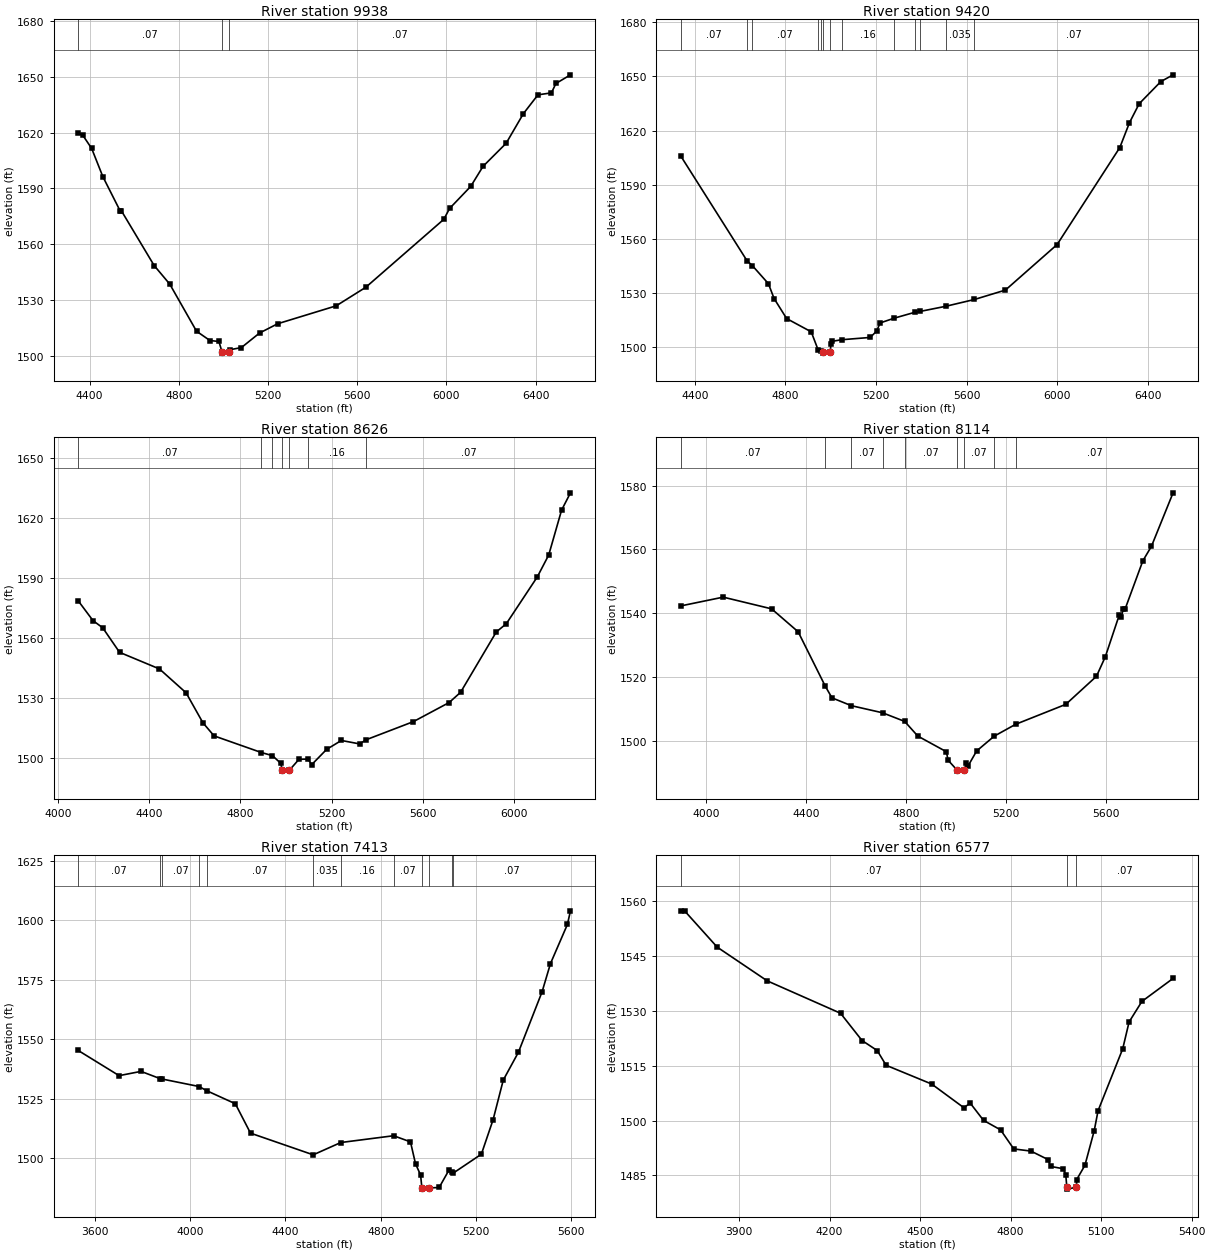
Type RM Length L Ch R = 1,9938,518,518,518
BEGIN DESCRIPTION:
Mapping XS cfc939a1
END DESCRIPTION:
XS GIS Cut Line= 3
      1653804.45      6991919.15      1654455.48      6991898.32
      1655989.37      6991637.90
#Sta/Elev= 30
  4349.1 1619.83  4369.7 1618.61  4409.7 1611.46  4459.7 1596.33  4538.1 1577.69
  4543.1 1577.90  4689.8 1548.49  4759.9 1538.46  4879.9 1513.14  4939.9 1508.14
  4980.0 1507.63  4994.6 1501.86  4995.1 1501.36  5025.7 1501.86  5028.8 1503.16
  5081.1 1504.36  5162.3 1512.17  5243.4 1517.16  5506.1 1526.81  5639.0 1536.81
  5988.5 1573.35  6014.3 1579.18  6109.1 1591.06  6164.4 1601.85  6267.9 1614.26
  6345.3 1630.21  6410.6 1640.32  6470.9 1641.37  6491.0 1646.42  6556.3 1651.08
#Mann=3,-1,0
  4349.1    0.07       0  4994.6    0.07       0  5025.7    0.07       0
Bank Sta=4994.6,5025.7
Exp/Cntr=0.3,0.1

Type RM Length L Ch R = 1,9420,794,794,794
BEGIN DESCRIPTION:
Mapping XS d5e20e84
END DESCRIPTION:
XS GIS Cut Line= 3
      1653885.18      6992169.16      1654502.35      6992398.32
      1655804.42      6993171.75
#Sta/Elev= 30
  4338.5 1605.90  4631.2 1547.76  4654.4 1545.11  4725.3 1535.08  4750.4 1526.85
  4805.8 1515.73  4914.3 1508.38  4944.9 1498.32  4957.5 1497.50  4967.0 1497.06
  4967.5 1496.56  4998.3 1497.06  5001.3 1501.74  5005.9 1503.09  5048.4 1503.99
  5174.4 1505.26  5202.6 1508.70  5218.3 1513.29  5280.5 1515.95  5372.2 1519.23
  5393.9 1519.67  5507.2 1522.51  5634.6 1526.31  5771.5 1531.54  5999.5 1556.78
  6276.2 1610.57  6319.0 1624.41  6361.8 1634.90  6457.3 1647.18  6511.3 1650.92
#Mann=13,-1,0
  4338.5    0.07       0  4631.2   0.035       0  4654.4    0.07       0
  4944.9   0.035       0  4957.5    0.07       0  4967.0    0.07       0
  4998.3    0.07       0  5048.4    0.16       0  5280.5    0.07       0
  5372.2    0.16       0  5393.9    0.07       0  5507.2   0.035       0
  5634.6    0.07       0
Bank Sta=4967,4998.3
Exp/Cntr=0.3,0.1

Type RM Length L Ch R = 1,8626,512,512,512
BEGIN DESCRIPTION:
Mapping XS ed869a84
END DESCRIPTION:
XS GIS Cut Line= 3
      1653846.29      6992347.64      1654318.50      6993132.35
      1655054.58      6994132.31
#Sta/Elev= 30
  4089.7 1578.78  4154.7 1568.86  4197.4 1565.26  4271.2 1553.01  4446.0 1544.71
  4562.6 1532.80  4636.4 1517.82  4685.3 1511.27  4892.8 1502.94  4941.2 1501.40
  4977.1 1497.60  4984.4 1494.16  4984.9 1493.66  5015.8 1494.16  5057.3 1499.55
  5095.9 1499.69  5113.7 1496.96  5178.5 1504.52  5243.2 1508.98  5322.7 1507.27
  5353.0 1509.39  5558.7 1518.38  5715.3 1527.91  5765.5 1533.01  5922.1 1563.18
  5966.0 1567.29  6101.8 1590.68  6151.9 1601.63  6208.3 1624.06  6247.2 1632.69
#Mann=7,-1,0
  4089.7    0.07       0  4892.8    0.16       0  4941.2    0.07       0
  4984.4    0.07       0  5015.8    0.07       0  5095.9    0.16       0
  5353.0    0.07       0
Bank Sta=4984.4,5015.8
Exp/Cntr=0.3,0.1

Type RM Length L Ch R = 1,8114,701,701,701
BEGIN DESCRIPTION:
Mapping XS cd522ee1
END DESCRIPTION:
XS GIS Cut Line= 3
      1653489.95      6992704.33      1654151.40      6993584.52
      1654670.36      6994282.52
#Sta/Elev= 30
  3898.4 1542.30  4068.4 1545.05  4262.1 1541.38  4368.3 1534.19  4476.9 1517.14
  4503.7 1513.48  4581.1 1511.03  4706.1 1508.80  4794.9 1506.09  4847.3 1501.50
  4961.9 1496.58  4968.2 1493.96  5002.4 1491.01  5002.9 1490.51  5033.8 1491.01
  5041.1 1493.17  5047.4 1491.98  5082.8 1496.82  5153.0 1501.46  5239.0 1505.19
  5439.9 1511.45  5562.6 1520.25  5598.0 1526.36  5654.3 1539.57  5662.7 1538.76
  5669.0 1541.37  5676.7 1541.22  5748.2 1556.43  5782.6 1560.98  5869.2 1577.75
#Mann=9,-1,0
  3898.4    0.07       0  4476.9    0.16       0  4581.1    0.07       0
  4706.1    0.16       0  4794.9    0.07       0  5002.4    0.07       0
  5033.8    0.07       0  5153.0    0.16       0  5239.0    0.07       0
Bank Sta=5002.4,5033.8
Exp/Cntr=0.3,0.1

Type RM Length L Ch R = 1,7413,836,836,836
BEGIN DESCRIPTION:
Mapping XS ae21f678
END DESCRIPTION:
XS GIS Cut Line= 3
      1652877.94      6993141.78      1653909.21      6994191.29
      1654305.05      6994636.60
#Sta/Elev= 30
  3529.6 1545.26  3701.6 1534.64  3793.5 1536.44  3874.7 1533.35  3883.6 1533.19
  4037.4 1530.07  4068.8 1528.33  4189.5 1522.82  4253.3 1510.44  4516.6 1501.31
  4632.4 1506.49  4854.3 1509.35  4925.0 1506.76  4946.2 1497.53  4967.5 1492.81
  4972.9 1487.37  4973.4 1486.87  5004.4 1487.37  5045.4 1487.56  5088.0 1495.12
  5098.5 1494.00  5102.7 1493.49  5222.7 1501.58  5272.0 1516.13  5314.6 1532.77
  5378.2 1544.48  5477.7 1569.97  5512.8 1581.82  5583.9 1598.29  5596.8 1604.03
#Mann=12,-1,0
  3529.6    0.07       0  3874.7   0.035       0  3883.6    0.07       0
  4037.4   0.035       0  4068.8    0.07       0  4516.6   0.035       0
  4632.4    0.16       0  4854.3    0.07       0  4972.9    0.07       0
  5004.4    0.07       0  5098.5    0.16       0  5102.7    0.07       0
Bank Sta=4972.9,5004.4
Exp/Cntr=0.3,0.1

Type RM Length L Ch R = 1,6577,580,580,580
BEGIN DESCRIPTION:
Mapping XS 4282063a
END DESCRIPTION:
XS GIS Cut Line= 3
      1652551.51      6993492.28      1653308.43      6994544.33
      1653485.49      6994829.01
#Sta/Elev= 30
  3707.1 1557.34  3721.0 1557.22  3827.8 1547.42  3993.5 1538.20  4236.5 1529.34
  4307.7 1521.89  4358.0 1519.15  4387.5 1515.12  4538.5 1509.99  4645.3 1503.51
  4666.1 1504.79  4710.3 1500.06  4766.8 1497.46  4810.6 1492.25  4867.4 1491.66
  4923.9 1489.35  4932.5 1487.47  4974.2 1486.84  4982.8 1485.24  4986.4 1481.76
  4986.9 1481.26  5018.3 1481.76  5019.2 1483.89  5046.3 1487.77  5077.0 1497.19
  5089.9 1502.70  5171.5 1519.60  5192.7 1526.97  5235.2 1532.58  5338.4 1538.86
#Mann=3,-1,0
  3707.1    0.07       0  4986.4    0.07       0  5018.3    0.07       0
Bank Sta=4986.4,5018.3
Exp/Cntr=0.3,0.1

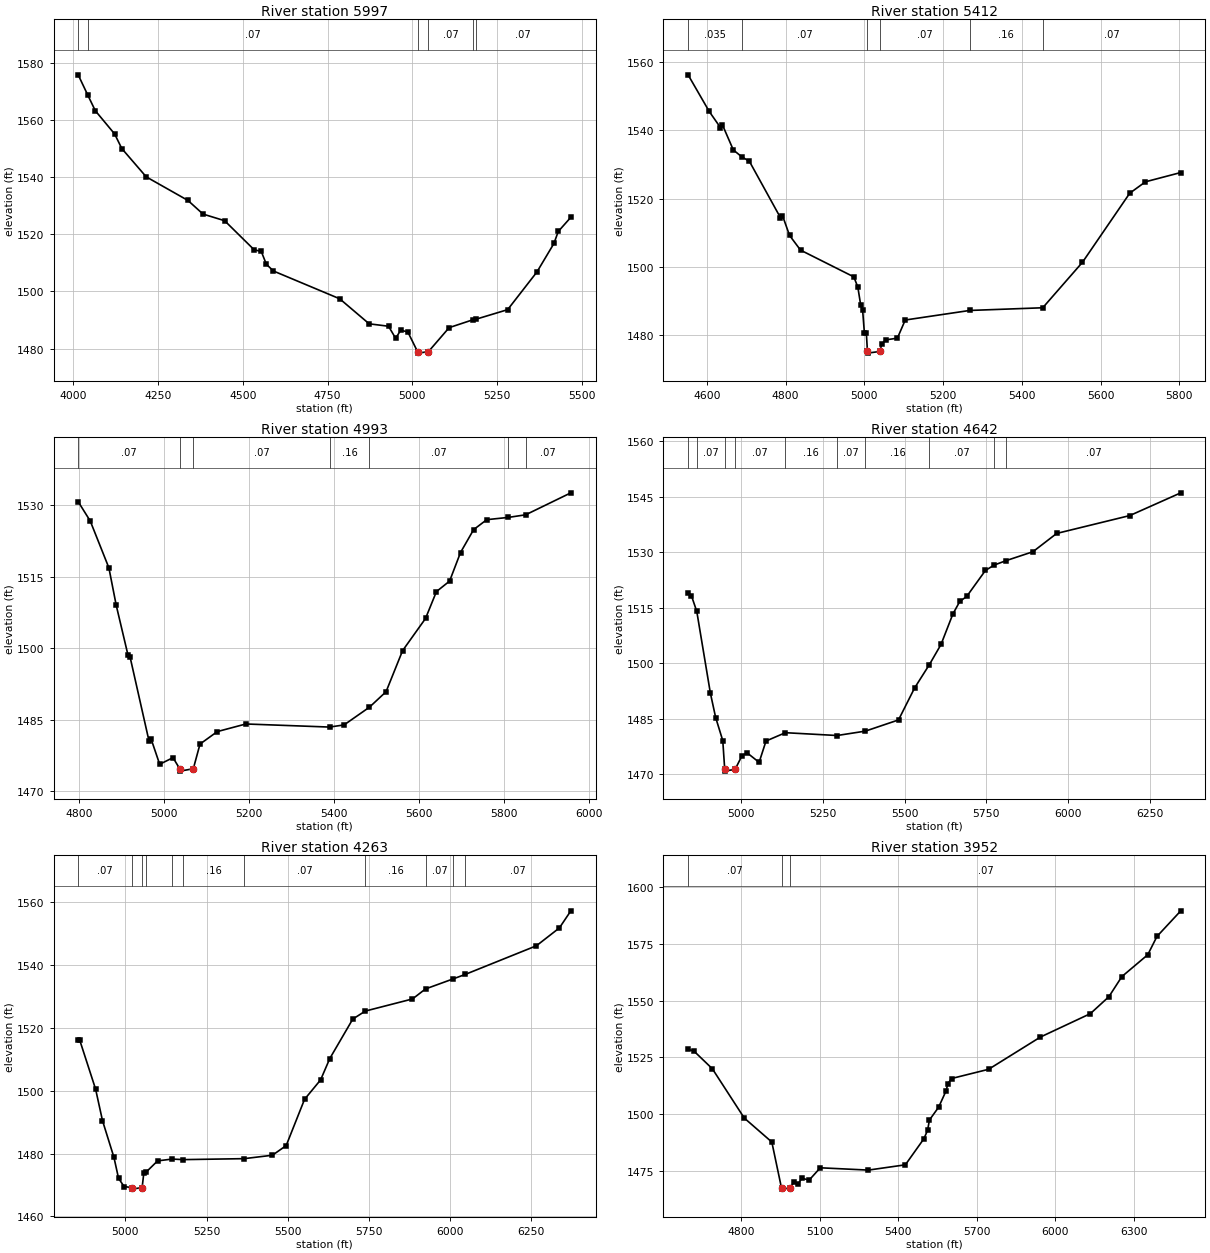
Type RM Length L Ch R = 1,5997,585,585,585
BEGIN DESCRIPTION:
Mapping XS 1d47ea10
END DESCRIPTION:
XS GIS Cut Line= 3
      1652211.18      6993822.07      1652759.82      6994641.55
      1653134.86      6994919.35
#Sta/Elev= 30
  4014.7 1575.74  4043.3 1568.58  4065.2 1563.19  4122.3 1555.04  4143.3 1549.97
  4215.4 1540.06  4338.4 1531.81  4382.9 1527.04  4446.5 1524.73  4533.6 1514.56
  4554.6 1513.98  4569.6 1509.50  4590.6 1507.13  4785.8 1497.43  4872.8 1488.67
  4929.9 1487.82  4950.9 1483.60  4965.9 1486.45  4986.9 1485.81  5015.5 1478.92
  5016.0 1478.42  5047.4 1478.92  5108.6 1487.33  5179.8 1490.13  5187.0 1490.25
  5281.1 1493.62  5367.5 1506.80  5417.6 1516.76  5430.4 1520.97  5467.6 1525.93
#Mann=6,-1,0
  4014.7    0.16       0  4043.3    0.07       0  5015.5    0.07       0
  5047.4    0.07       0  5179.8    0.16       0  5187.0    0.07       0
Bank Sta=5015.5,5047.4
Exp/Cntr=0.3,0.1

Type RM Length L Ch R = 1,5412,419,419,419
BEGIN DESCRIPTION:
Mapping XS 3a03f0e4
END DESCRIPTION:
XS GIS Cut Line= 3
      1651872.42      6994896.22      1652312.48      6994984.76
      1653114.59      6994989.97
#Sta/Elev= 30
  4552.5 1556.35  4606.1 1545.60  4634.6 1540.86  4639.7 1541.66  4667.3 1534.29
  4688.6 1532.27  4708.1 1530.95  4787.1 1514.36  4792.2 1515.00  4810.1 1509.17
  4838.0 1504.84  4973.3 1496.98  4983.5 1493.99  4990.6 1488.83  4995.7 1487.17
  5000.1 1480.57  5005.1 1480.57  5007.9 1475.07  5008.4 1474.57  5039.9 1475.07
  5043.9 1477.23  5053.9 1478.46  5083.9 1478.96  5103.9 1484.30  5267.6 1487.11
  5453.0 1487.90  5553.9 1501.27  5673.9 1521.56  5713.9 1524.92  5803.5 1527.64
#Mann=6,-1,0
  4552.5   0.035       0  4688.6    0.07       0  5007.9    0.07       0
  5039.9    0.07       0  5267.6    0.16       0  5453.0    0.07       0
Bank Sta=5007.9,5039.9
Exp/Cntr=0.3,0.1

Type RM Length L Ch R = 1,4993,351,351,351
BEGIN DESCRIPTION:
Mapping XS 33fbc6fc
END DESCRIPTION:
XS GIS Cut Line= 3
      1652057.25      6995427.47      1652255.19      6995385.80
      1653158.88      6995068.07
#Sta/Elev= 30
  4798.0 1530.78  4826.4 1526.72  4870.3 1516.88  4887.7 1508.96  4915.0 1498.65
  4920.1 1498.18  4964.8 1480.48  4969.9 1480.86  4989.9 1475.59  5021.3 1476.98
  5037.1 1474.65  5037.6 1474.15  5069.1 1474.65  5084.9 1479.84  5125.6 1482.46
  5192.9 1484.06  5389.9 1483.41  5424.1 1483.86  5483.9 1487.59  5523.0 1490.84
  5561.9 1499.47  5615.9 1506.23  5641.6 1511.88  5672.6 1514.09  5698.3 1520.09
  5729.2 1524.91  5760.2 1527.00  5810.5 1527.47  5851.7 1528.02  5958.2 1532.64
#Mann=7,-1,0
  4798.0    0.07       0  5037.1    0.07       0  5069.1    0.07       0
  5389.9    0.16       0  5483.9    0.07       0  5810.5    0.16       0
  5851.7    0.07       0
Bank Sta=5037.1,5069.1
Exp/Cntr=0.3,0.1

Type RM Length L Ch R = 1,4642,379,379,379
BEGIN DESCRIPTION:
Mapping XS 8ae0ccfb
END DESCRIPTION:
XS GIS Cut Line= 3
      1652255.85      6995763.51      1652401.72      6995683.63
      1653530.13      6994957.97
#Sta/Elev= 30
  4837.0 1519.07  4847.4 1518.24  4863.6 1514.05  4905.3 1491.94  4921.4 1485.38
  4943.2 1479.13  4949.1 1471.40  4949.6 1470.90  4981.1 1471.40  5002.3 1475.12
  5018.1 1475.81  5054.4 1473.27  5075.5 1479.03  5134.8 1481.28  5293.1 1480.52
  5379.8 1481.71  5481.0 1484.73  5530.3 1493.37  5575.5 1499.67  5611.1 1505.11
  5647.4 1513.34  5668.5 1516.72  5689.7 1518.08  5747.1 1525.11  5773.7 1526.55
  5809.7 1527.74  5892.4 1530.16  5965.1 1535.10  6188.9 1539.93  6344.9 1546.07
#Mann=10,-1,0
  4837.0    0.16       0  4863.6    0.07       0  4949.1    0.07       0
  4981.1    0.07       0  5134.8    0.16       0  5293.1    0.07       0
  5379.8    0.16       0  5575.5    0.07       0  5773.7    0.16       0
  5809.7    0.07       0
Bank Sta=4949.1,4981.1
Exp/Cntr=0.3,0.1

Type RM Length L Ch R = 1,4263,311,311,311
BEGIN DESCRIPTION:
Mapping XS aeec1e15
END DESCRIPTION:
XS GIS Cut Line= 3
      1652533.63      6996072.55      1652634.36      6995971.82
      1653623.94      6995016.96
#Sta/Elev= 30
  4854.5 1516.20  4859.0 1516.20  4908.2 1500.50  4929.4 1490.49  4964.7 1478.79
  4978.9 1472.11  4996.1 1469.50  5019.5 1469.19  5020.0 1468.69  5051.5 1469.19
  5056.6 1473.76  5063.8 1474.11  5099.1 1477.68  5143.8 1478.26  5177.9 1478.08
  5365.8 1478.39  5452.8 1479.48  5495.2 1482.55  5551.8 1497.28  5601.2 1503.46
  5629.5 1510.26  5700.3 1522.81  5738.8 1525.36  5884.2 1529.22  5924.4 1532.41
  6009.6 1535.61  6047.0 1537.04  6266.0 1546.15  6336.7 1551.83  6372.1 1557.27
#Mann=11,-1,0
  4854.5    0.07       0  5019.5    0.07       0  5051.5    0.07       0
  5063.8    0.16       0  5143.8    0.07       0  5177.9    0.16       0
  5365.8    0.07       0  5738.8    0.16       0  5924.4    0.07       0
  6009.6    0.16       0  6047.0    0.07       0
Bank Sta=5019.5,5051.5
Exp/Cntr=0.3,0.1

Type RM Length L Ch R = 1,3952,435,435,435
BEGIN DESCRIPTION:
Mapping XS 1780a849
END DESCRIPTION:
XS GIS Cut Line= 3
      1652832.27      6996489.23      1652905.19      6996093.35
      1653932.98      6995027.37
#Sta/Elev= 30
  4596.9 1528.53  4618.5 1527.90  4689.7 1520.01  4811.7 1498.28  4917.0 1487.71
  4954.0 1467.44  4954.5 1466.94  4986.0 1467.44  5003.1 1470.23  5017.3 1469.05
  5031.4 1471.77  5059.7 1470.92  5102.2 1476.35  5285.9 1475.33  5427.4 1477.66
  5498.1 1489.13  5512.3 1492.85  5519.5 1497.43  5554.7 1503.08  5583.0 1510.27
  5590.2 1513.51  5604.2 1515.72  5745.6 1519.78  5943.7 1534.00  6134.6 1544.32
  6205.3 1551.78  6255.0 1560.66  6354.0 1570.30  6389.3 1578.39  6480.2 1589.66
#Mann=3,-1,0
  4596.9    0.07       0  4954.0    0.07       0  4986.0    0.07       0
Bank Sta=4954,4986
Exp/Cntr=0.3,0.1

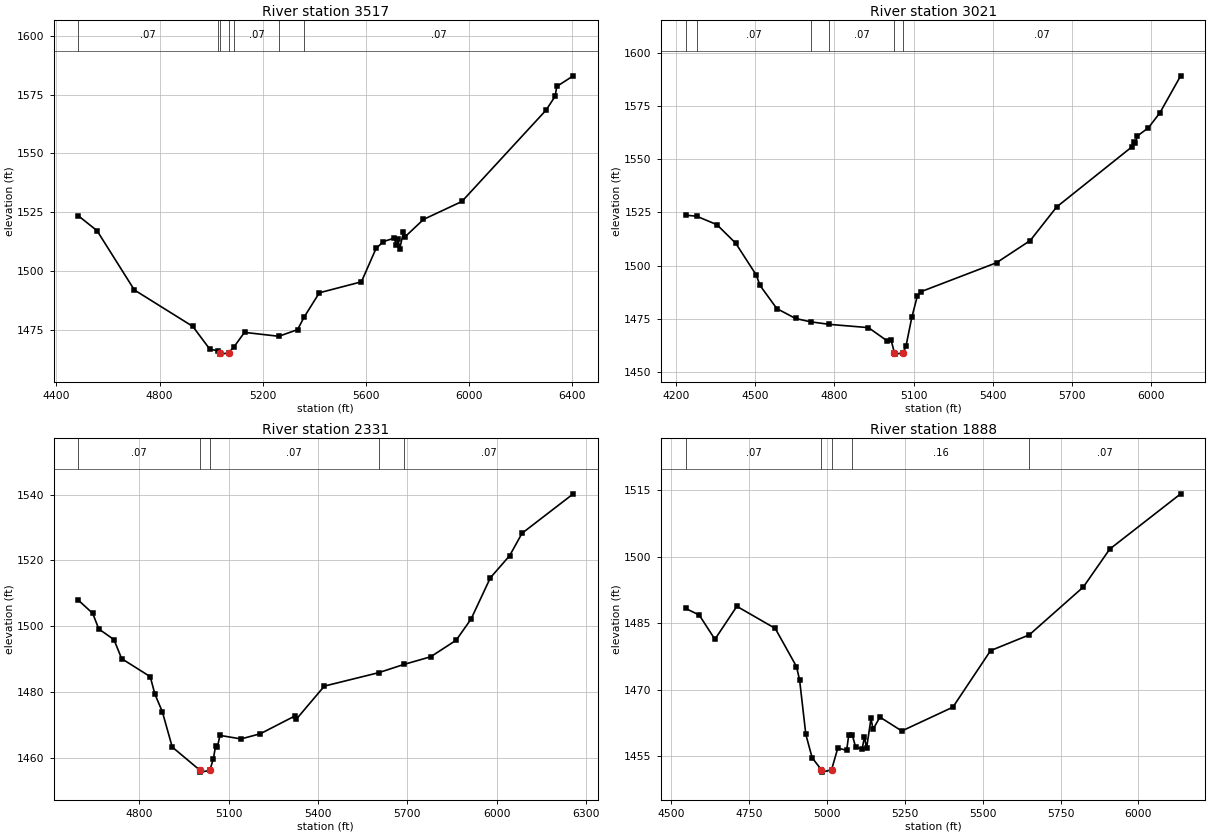
Type RM Length L Ch R = 1,3517,496,496,496
BEGIN DESCRIPTION:
Mapping XS f852f67f
END DESCRIPTION:
XS GIS Cut Line= 3
      1653030.88      6996631.55      1653286.09      6996194.05
      1654343.40      6995256.53
#Sta/Elev= 30
  4484.6 1523.45  4557.3 1517.10  4702.0 1491.87  4928.6 1476.37  4994.5 1466.69
  5027.4 1465.93  5035.3 1465.07  5035.8 1464.57  5067.4 1465.07  5088.5 1467.67
  5129.2 1473.83  5262.1 1472.16  5334.9 1474.99  5359.9 1480.23  5419.4 1490.67
  5582.5 1495.34  5639.3 1509.52  5667.8 1512.46  5710.4 1513.97  5717.1 1510.87
  5724.6 1513.37  5731.3 1509.49  5745.5 1516.39  5752.2 1514.54  5823.3 1521.89
  5972.2 1529.53  6298.4 1568.37  6333.5 1574.24  6340.2 1578.48  6404.2 1583.00
#Mann=7,-1,0
  4484.6    0.07       0  5027.4   0.035       0  5035.3    0.07       0
  5067.4   0.035       0  5088.5    0.07       0  5262.1    0.16       0
  5359.9    0.07       0
Bank Sta=5035.3,5067.4
Exp/Cntr=0.3,0.1

Type RM Length L Ch R = 1,3021,690,690,690
BEGIN DESCRIPTION:
Mapping XS da2a4316
END DESCRIPTION:
XS GIS Cut Line= 3
      1653140.25      6996850.30      1653702.76      6996350.30
      1654581.06      6995653.89
#Sta/Elev= 30
  4237.4 1523.62  4278.6 1523.17  4355.6 1519.18  4426.7 1510.48  4504.5 1495.54
  4518.7 1490.66  4582.2 1479.81  4653.3 1475.13  4709.9 1473.58  4781.2 1472.37
  4929.3 1470.84  5000.5 1464.57  5014.9 1465.02  5027.7 1458.90  5028.2 1458.40
  5059.9 1458.90  5071.0 1462.03  5093.5 1475.76  5114.3 1485.74  5128.7 1487.75
  5413.9 1501.31  5541.6 1511.74  5641.5 1527.49  5925.0 1555.58  5933.1 1557.98
  5939.5 1557.56  5947.5 1560.84  5989.1 1564.72  6032.4 1571.71  6110.9 1589.06
#Mann=6,-1,0
  4237.4   0.035       0  4278.6    0.07       0  4709.9   0.035       0
  4781.2    0.07       0  5027.7    0.07       0  5059.9    0.07       0
Bank Sta=5027.7,5059.9
Exp/Cntr=0.3,0.1

Type RM Length L Ch R = 1,2331,443,443,443
BEGIN DESCRIPTION:
Mapping XS 3a7e0226
END DESCRIPTION:
XS GIS Cut Line= 3
      1653407.28      6997049.25      1653806.58      6996976.34
      1654817.01      6996229.80
#Sta/Elev= 30
  4594.8 1507.89  4643.3 1503.85  4663.6 1499.11  4714.5 1495.89  4740.4 1490.08
  4836.4 1484.60  4852.0 1479.30  4877.1 1473.90  4910.3 1463.18  5004.2 1456.05
  5004.7 1455.55  5036.4 1456.05  5048.5 1459.68  5055.7 1463.40  5062.0 1463.17
  5070.4 1466.73  5141.3 1465.65  5206.1 1467.23  5320.9 1472.58  5327.1 1471.67
  5421.1 1481.73  5603.7 1485.82  5687.9 1488.31  5778.1 1490.65  5863.7 1495.69
  5913.8 1502.14  5978.6 1514.70  6043.1 1521.39  6085.0 1528.25  6257.0 1540.24
#Mann=5,-1,0
  4594.8    0.07       0  5004.2    0.07       0  5036.4    0.07       0
  5603.7    0.16       0  5687.9    0.07       0
Bank Sta=5004.2,5036.4
Exp/Cntr=0.3,0.1

Type RM Length L Ch R = 1,1888,454,454,454
BEGIN DESCRIPTION:
Swager Creek 3.0
END DESCRIPTION:
XS GIS Cut Line= 3
      1653661.76      6997344.05      1654111.66      6997294.68
      1654980.00      6996563.00
#Sta/Elev= 30
  4547.4 1488.37  4590.9 1486.89  4641.2 1481.41  4711.6 1488.85  4834.7 1483.87
  4902.8 1475.28  4912.8 1472.29  4932.9 1459.96  4953.1 1454.71  4983.1 1451.96
  4983.6 1451.46  5015.3 1451.96  5035.4 1456.86  5063.9 1456.40  5070.5 1459.79
  5081.6 1459.93  5092.5 1457.14  5113.4 1456.60  5121.1 1459.45  5127.7 1456.81
  5142.0 1463.56  5148.5 1461.11  5170.6 1463.87  5240.8 1460.74  5404.7 1466.11
  5525.6 1478.86  5649.7 1482.41  5823.4 1493.22  5908.0 1501.76  6135.5 1514.22
#Mann=5,-1,0
  4547.4    0.07       0  4983.1    0.07       0  5015.3    0.07       0
  5081.6    0.16       0  5649.7    0.07       0
Bank Sta=4983.1,5015.3
Exp/Cntr=0.3,0.1