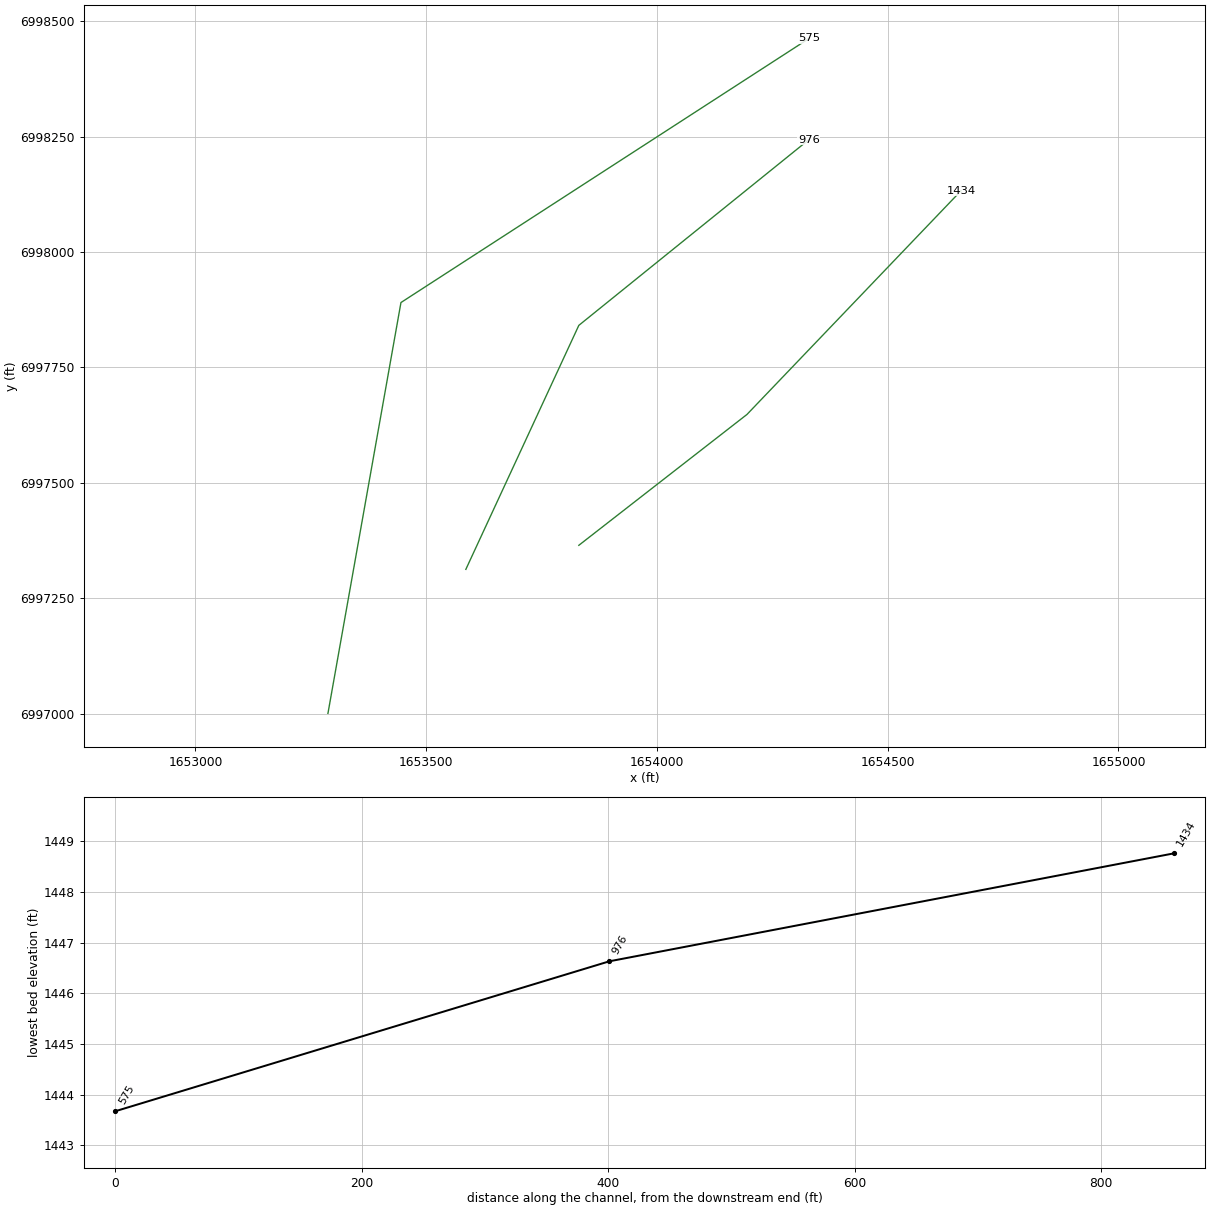
HEC-RAS study Swager Creek.prj: Swager Creek Base Level Engineering

--- Swager Creek.g01 (geometry) --- (continued)

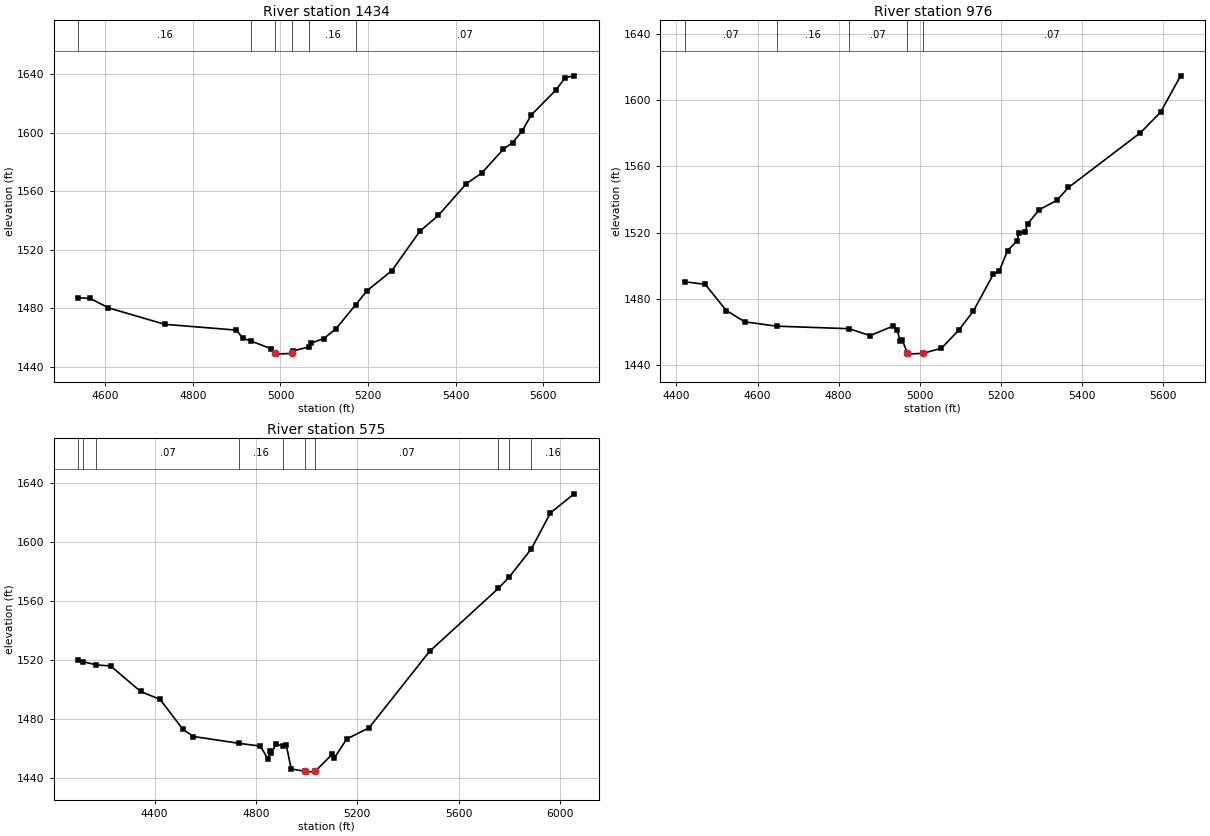
Type RM Length L Ch R = 1,1434,458,458,458
BEGIN DESCRIPTION:
Swager Creek 2.0
END DESCRIPTION:
XS GIS Cut Line= 3
      1653830.77      6997364.47      1654195.12      6997648.05
      1654658.89      6998132.70
#Sta/Elev= 30
  4538.3 1487.27  4565.6 1486.78  4607.2 1480.37  4735.7 1469.13  4899.4 1465.16
  4913.9 1459.67  4931.6 1457.79  4978.2 1452.52  4987.8 1449.26  4988.8 1448.76
  5026.2 1449.26  5028.0 1450.86  5065.0 1453.70  5070.5 1456.37  5098.8 1459.38
  5127.1 1466.20  5172.3 1482.67  5197.9 1492.13  5254.5 1505.83  5318.3 1532.71
  5360.5 1543.51  5424.3 1565.14  5459.5 1572.44  5509.2 1588.80  5530.3 1593.33
  5551.7 1601.05  5572.7 1612.10  5629.4 1629.30  5650.4 1637.66  5670.8 1638.92
#Mann=6,-1,0
  4538.3    0.16       0  4931.6    0.07       0  4987.8    0.07       0
  5026.2    0.07       0  5065.0    0.16       0  5172.3    0.07       0
Bank Sta=4987.8,5026.2
Exp/Cntr=0.3,0.1

Type RM Length L Ch R = 1,976,401,401,401
BEGIN DESCRIPTION:
Mapping XS bbc830fe
END DESCRIPTION:
XS GIS Cut Line= 3
      1653585.94      6997312.35      1653830.75      6997841.02
      1654329.35      6998243.54
#Sta/Elev= 30
  4420.5 1490.33  4470.8 1488.77  4522.9 1472.96  4568.7 1466.13  4647.1 1463.52
  4826.1 1461.98  4877.7 1457.81  4934.5 1463.59  4944.7 1461.10  4952.0 1454.33
  4957.5 1455.06  4969.6 1447.13  4970.6 1446.63  5008.0 1447.13  5053.8 1450.18
  5096.9 1461.23  5132.1 1472.50  5181.7 1494.77  5196.1 1496.56  5216.9 1509.18
  5239.3 1514.81  5245.7 1519.96  5260.1 1520.56  5266.5 1525.35  5295.3 1533.89
  5338.4 1539.47  5367.2 1547.27  5544.7 1580.33  5594.3 1592.69  5643.9 1614.70
#Mann=5,-1,0
  4420.5    0.07       0  4647.1    0.16       0  4826.1    0.07       0
  4969.6    0.07       0  5008.0    0.07       0
Bank Sta=4969.6,5008
Exp/Cntr=0.3,0.1

Type RM Length L Ch R = 1,575,0,0,0
BEGIN DESCRIPTION:
Mapping XS 8d9c6b2e
END DESCRIPTION:
XS GIS Cut Line= 3
      1653287.14      6997000.28      1653445.33      6997890.50
      1654329.99      6998462.99
#Sta/Elev= 30
  4098.5 1519.57  4118.6 1518.54  4169.2 1516.43  4226.2 1515.70  4344.3 1498.39
  4421.2 1493.04  4511.2 1472.75  4553.2 1467.83  4732.0 1463.24  4817.3 1461.33
  4847.8 1452.42  4855.4 1457.88  4860.5 1456.44  4878.2 1462.50  4906.1 1461.59
  4919.5 1461.97  4939.2 1445.86  4995.0 1444.17  4996.0 1443.67  5033.4 1444.17
  5101.4 1455.87  5109.5 1453.31  5158.8 1466.22  5246.5 1473.74  5485.3 1525.60
  5757.2 1568.36  5799.7 1576.05  5887.4 1595.16  5962.8 1619.62  6056.4 1632.52
#Mann=10,-1,0
  4098.5    0.07       0  4118.6    0.16       0  4169.2    0.07       0
  4732.0    0.16       0  4906.1    0.07       0  4995.0    0.07       0
  5033.4    0.07       0  5757.2    0.16       0  5799.7    0.07       0
  5887.4    0.16       0
Bank Sta=4995,5033.4
Exp/Cntr=0.3,0.1

Chan Stop Cuts=-1