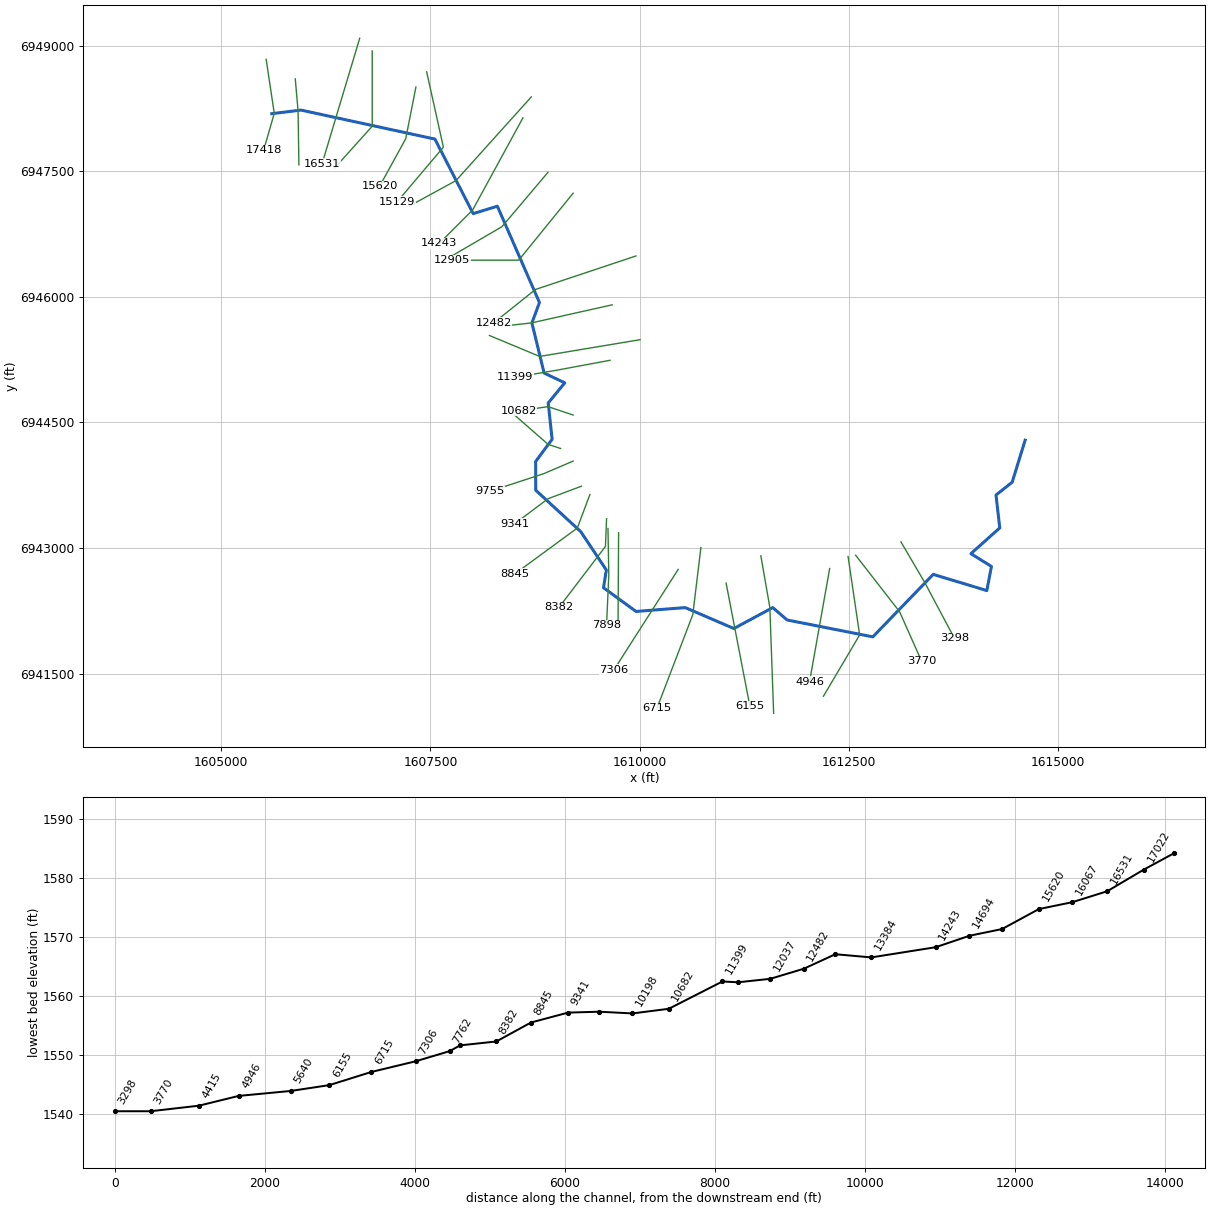
--- Deadman 01.prj (project) ---

Proj Title=Deadman 01 Base Level Engineering
Current Plan=p01
Default Exp/Contr=0.3,0.1
English Units
Geom File=g01
Flow File=f01
Plan File=p01
Y Axis Title=Elevation
X Axis Title(PF)=Main Channel Distance
X Axis Title(XS)=Station
BEGIN DESCRIPTION:
Deadman 01
END DESCRIPTION:
DSS Export Rating Curves= 0
DSS Export Rating Curve Sorted= 0
DSS Export Volume Flow Curves= 0
DXF OffsetX= 0
DXF OffsetY= 0
DXF ScaleX= 1
DXF ScaleY= 10

--- Deadman 01.p01 (plan) ---

Plan Title=Multiple Run
Short Identifier=Multiple
Geom File=g01
Flow File=f01
Subcritical Flow
K Sum by GR= 0
Std Step Tol= 0.01
Critical Tol= 0.01
Num of Std Step Trials= 20
Max Error Tol= 0.3
Flow Tol Ratio= 0.001
Split Flow NTrial= 30
Split Flow Tol= 0.02
Split Flow Ratio= 0.02
Log Output Level= 0
Friction Slope Method= 1
Unsteady Friction Slope Method= 2
Unsteady Bridges Friction Slope Method= 1
Parabolic Critical Depth
Global Vel Dist=  1 , 1 , 1
Global Log Level= 0
CheckData=True
Encroach Param= -1, 0, 0, 0
BEGIN DESCRIPTION:
Multiple Run
END DESCRIPTION:

--- Deadman 01.f01 (steady flow) ---

Flow Title=Multiple
Number of Profiles=7
Profile Names=10-year,25-year,50-year,1pct_min,100-year,1pct_plu,500-year
River Rch & RM= Deadman 01,Reach-1,17418
     335     468     578     355     708    1413    1079
River Rch & RM= Deadman 01,Reach-1,14694
     438     620     773     479     956    1907    1481
River Rch & RM= Deadman 01,Reach-1,12482
     480     677     843     521    1040    2074    1602
River Rch & RM= Deadman 01,Reach-1,4415
     516     730     909     563    1123    2240    1734
Boundary for River Rch & Prof#=Deadman 01,Reach-1,1
Up Type=0
Dn Type=3
Dn Slope=0.005
Boundary for River Rch & Prof#=Deadman 01,Reach-1,2
Up Type=0
Dn Type=3
Dn Slope=0.005
Boundary for River Rch & Prof#=Deadman 01,Reach-1,3
Up Type=0
Dn Type=3
Dn Slope=0.005
Boundary for River Rch & Prof#=Deadman 01,Reach-1,4
Up Type=0
Dn Type=3
Dn Slope=0.005
Boundary for River Rch & Prof#=Deadman 01,Reach-1,5
Up Type=0
Dn Type=3
Dn Slope=0.005
Boundary for River Rch & Prof#=Deadman 01,Reach-1,6
Up Type=0
Dn Type=3
Dn Slope=0.005
Boundary for River Rch & Prof#=Deadman 01,Reach-1,7
Up Type=0
Dn Type=3
Dn Slope=0.005

--- Deadman 01.g01 (geometry) ---

Geom Title=Existing Conditions
Program Version=4.10

River Reach=Deadman 01      ,Reach-1
Reach XY= 30
        1605605.        6948188.      1605954.91      6948230.69
      1607553.55      6947884.47      1608010.92      6946993.67
      1608299.53      6947082.74      1608802.75      6945932.06
       1608712.3      6945688.08      1608858.45      6945089.19
      1609105.11      6944972.65      1608907.23       6944732.1
      1608953.96      6944298.44      1608756.59      6944031.95
      1608758.45      6943689.49      1609296.84      6943194.05
      1609601.54      6942736.51      1609567.98      6942524.43
       1609956.5      6942241.61      1610544.38       6942287.4
      1611125.16      6942037.54      1611589.78      6942287.76
      1611761.03      6942139.62      1612784.96      6941938.05
      1613506.46      6942684.47      1614146.99      6942490.83
      1614201.95      6942779.72      1613956.76      6942931.83
      1614301.55      6943239.48      1614256.62      6943631.97
      1614449.64       6943785.3        1614605.        6944288.

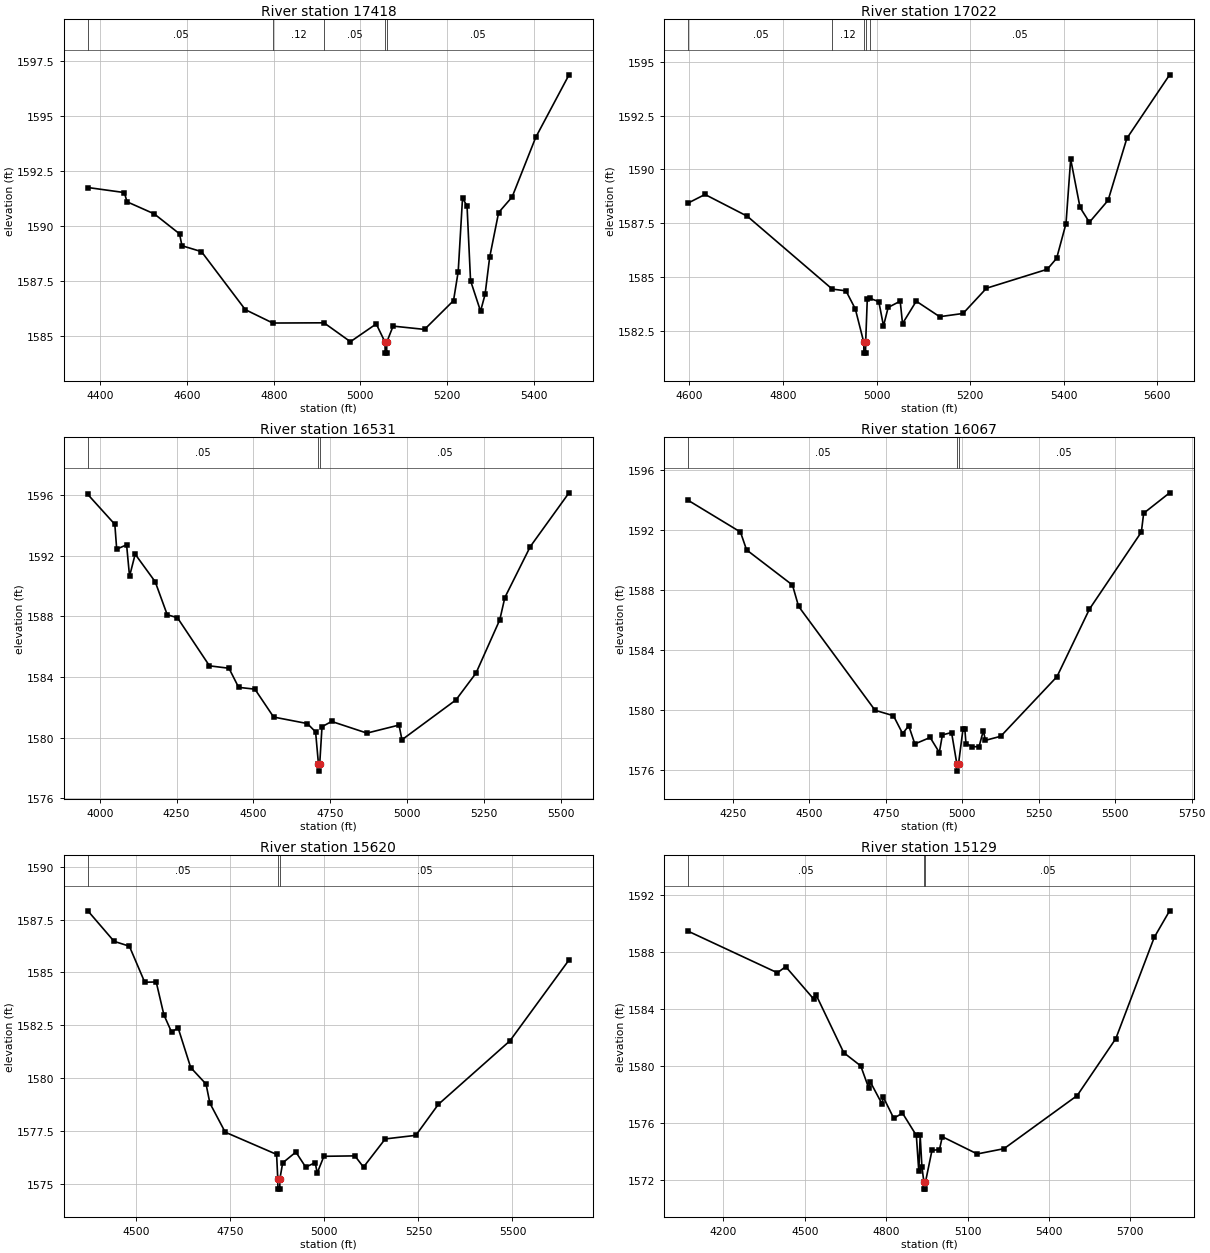
Type RM Length L Ch R = 1 ,17418   ,396,396,396
BEGIN DESCRIPTION:
Deadman 01 32.0
END DESCRIPTION:
XS GIS Cut Line= 3
      1605537.66      6948837.39      1605634.64      6948191.97
      1605507.93      6947751.81
#Sta/Elev= 30
  4370.8 1591.75    4455 1591.52  4461.2  1591.1    4524 1590.55  4582.5 1589.64
    4588  1589.1  4633.1 1588.83  4734.2 1586.19  4797.7 1585.58  4915.9 1585.59
  4976.9 1584.73  5036.5 1585.54  5056.8 1584.71  5057.1 1584.21  5060.6 1584.21
  5060.8 1584.71  5075.4 1585.44    5148 1585.29  5214.9  1586.6  5225.7 1587.92
  5235.7 1591.27  5246.1 1590.91  5254.2 1587.51  5277.3 1586.12  5287.7 1586.88
  5298.3 1588.57    5319 1590.61  5350.2 1591.32  5404.6 1594.03  5481.5 1596.88
#Mann= 5 ,-1 , 0
  4370.8     .05       0  4797.7     .12       0  4915.9     .05       0
  5056.8     .05       0  5060.8     .05       0
Bank Sta=5056.8,5060.8
XS Rating Curve= 0 ,0
Exp/Cntr=0.3,0.1

Type RM Length L Ch R = 1 ,17022   ,491,491,491
BEGIN DESCRIPTION:
Mapping XS 7f15ad65
END DESCRIPTION:
XS GIS Cut Line= 3
      1605885.46      6948603.29       1605918.9      6948222.06
      1605928.94      6947576.63
#Sta/Elev= 30
  4597.9 1588.45  4633.3 1588.84  4723.7 1587.83  4905.2 1584.45  4934.5 1584.37
  4954.5 1583.53  4972.6 1581.98  4972.9 1581.48  4976.4 1581.48  4976.6 1581.98
  4980.1    1584  4985.8 1584.02  5004.7 1583.87  5014.7 1582.74  5024.7  1583.6
  5050.4 1583.89  5055.4 1582.85  5084.7 1583.89  5134.7 1583.17  5184.7 1583.32
  5234.7 1584.49  5364.7 1585.37  5384.7 1585.88  5404.7 1587.49  5414.7 1590.48
  5434.7 1588.24  5454.7 1587.55  5494.7 1588.57  5534.7 1591.44  5626.1 1594.39
#Mann= 5 ,-1 , 0
  4597.9     .05       0  4905.2     .12       0  4972.6     .05       0
  4976.6     .12       0  4985.8     .05       0
Bank Sta=4972.6,4976.6
XS Rating Curve= 0 ,0
Exp/Cntr=0.3,0.1

Type RM Length L Ch R = 1 ,16531   ,464,464,464
BEGIN DESCRIPTION:
Deadman 01 31.0
END DESCRIPTION:
XS GIS Cut Line= 3
      1606654.99      6949087.98        1606355.        6948088.
      1606205.01      6947588.02
#Sta/Elev= 30
  3961.2 1596.05    4049 1594.08  4055.1 1592.44  4087.3 1592.73  4096.9 1590.65
  4115.2 1592.11  4180.4 1590.29  4219.6 1588.11  4252.6 1587.92    4357 1584.74
  4420.5 1584.58  4451.9 1583.32  4504.9  1583.2  4565.8 1581.36  4675.5 1580.93
  4702.4 1580.38  4711.6 1578.29  4711.9 1577.79  4715.9 1578.29  4723.3 1580.72
  4754.6 1581.07  4869.5  1580.3  4973.9 1580.83  4983.5 1579.86  5159.2 1582.49
  5224.5 1584.26  5301.9 1587.78  5318.4 1589.25  5401.1 1592.61  5527.2 1596.16
#Mann= 3 ,-1 , 0
  3961.2     .05       0  4711.6     .03       0  4715.9     .05       0
Bank Sta=4711.6,4715.9
XS Rating Curve= 0 ,0
Exp/Cntr=0.3,0.1

Type RM Length L Ch R = 1 ,16067   ,447,447,447
BEGIN DESCRIPTION:
Deadman 01 30.0
END DESCRIPTION:
XS GIS Cut Line= 3
        1606805.      6948937.96        1606805.        6948038.
      1606355.03      6947538.03
#Sta/Elev= 30
  4105.3 1593.96  4275.3 1591.86  4295.3 1590.67  4445.3 1588.33  4465.3 1586.91
  4715.3 1579.99  4775.3 1579.63  4805.3 1578.44  4825.3 1578.96  4845.3 1577.75
  4895.3 1578.18  4925.3 1577.18  4935.3 1578.35  4965.3 1578.51  4982.4 1576.44
  4982.9 1575.94  4988.1 1576.44  5002.8 1578.76  5008.6 1578.76  5012.4 1577.77
  5033.3 1577.57    5055 1577.56  5069.2 1578.64  5075.9 1577.99    5126 1578.26
  5309.8 1582.23    5416 1586.73  5585.6 1591.86  5593.1 1593.11  5677.9 1594.47
#Mann= 3 ,-1 , 0
  4105.3     .05       0  4982.4     .03       0  4988.1     .05       0
Bank Sta=4982.4,4988.1
XS Rating Curve= 0 ,0
Exp/Cntr=0.3,0.1

Type RM Length L Ch R = 1 ,15620   ,491,491,491
BEGIN DESCRIPTION:
Deadman 01 29.0
END DESCRIPTION:
XS GIS Cut Line= 3
      1607326.84      6948506.35        1607205.        6947888.
      1606892.08      6947319.12
#Sta/Elev= 30
  4370.9 1587.91  4440.6 1586.47  4481.3 1586.24  4522.1 1584.54  4552.7 1584.55
  4573.1    1583  4593.4 1582.19    4611 1582.38  4644.4 1580.51  4685.2 1579.73
  4695.4 1578.83  4736.1 1577.46  4872.8 1576.41  4875.9 1575.27  4876.4 1574.77
  4881.2 1574.77  4881.7 1575.27    4889 1576.01  4924.1 1576.52  4950.2 1575.81
  4975.5 1576.02  4980.8 1575.53  4998.6 1576.32    5081 1576.34  5103.9 1575.81
  5161.7 1577.14  5243.1 1577.31  5302.8 1578.77  5493.2 1581.77  5650.4 1585.59
#Mann= 3 ,-1 , 0
  4370.9     .05       0  4875.9     .03       0  4881.7     .05       0
Bank Sta=4875.9,4881.7
XS Rating Curve= 0 ,0
Exp/Cntr=0.3,0.1

Type RM Length L Ch R = 1 ,15129   ,435,435,435
BEGIN DESCRIPTION:
Deadman 01 28.0
END DESCRIPTION:
XS GIS Cut Line= 3
        1607455.      6948688.01        1607655.        6947788.
      1607105.02      6947138.03
#Sta/Elev= 30
  4071.3 1589.48  4399.1 1586.57  4429.8    1587  4532.3 1584.74  4542.5 1584.99
  4643.7 1580.96  4706.4 1580.03  4735.9 1578.47    4741 1578.93  4784.5 1577.37
  4789.7 1577.83  4828.1 1576.35  4860.1 1576.72  4911.3 1575.15  4920.3 1572.62
  4925.4 1575.15  4931.8 1572.95  4939.1 1571.88  4939.6 1571.38  4944.4 1571.38
  4944.9 1571.88  4968.9  1574.1  4996.5 1574.16    5007 1575.06  5135.6 1573.85
  5234.4 1574.22  5504.1 1577.95  5646.5 1581.95  5788.2 1589.06  5844.7 1590.92
#Mann= 3 ,-1 , 0
  4071.3     .05       0  4939.1     .05       0  4944.9     .05       0
Bank Sta=4939.1,4944.9
XS Rating Curve= 0 ,0
Exp/Cntr=0.3,0.1

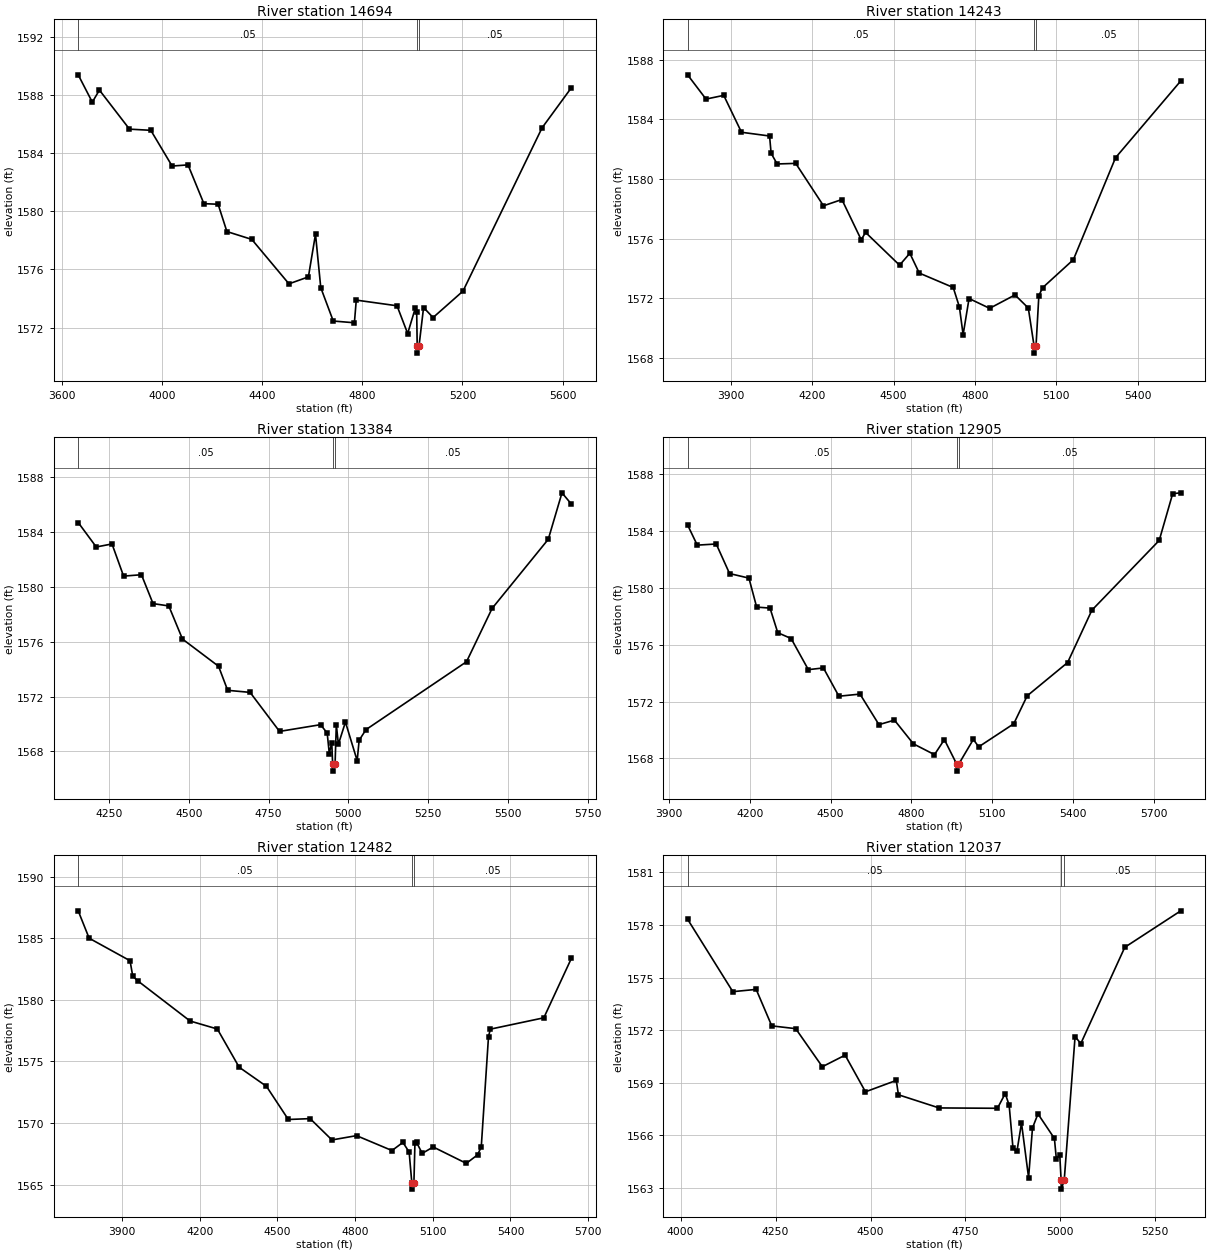
Type RM Length L Ch R = 1 ,14694   ,451,451,451
BEGIN DESCRIPTION:
Deadman 01 27.0
END DESCRIPTION:
XS GIS Cut Line= 3
      1608704.98      6948387.98        1607805.        6947388.
      1607255.03      6947088.01
#Sta/Elev= 30
  3663.6  1589.4    3720 1587.52  3748.4 1588.35  3868.7 1585.66  3953.9 1585.58
  4039.1 1583.12  4102.7  1583.2  4166.2 1580.53    4223 1580.49  4258.1 1578.61
  4357.6 1578.07  4506.3 1575.01    4584 1575.49  4612.4 1578.43  4633.4 1574.75
  4683.4 1572.45  4767.9 1572.33  4775.4 1573.89  4938.3  1573.5  4980.9 1571.59
  5011.8 1573.36    5017 1573.04    5019 1570.74  5019.5 1570.24  5026.3 1570.74
  5044.5 1573.38  5082.5 1572.69  5202.1 1574.51  5518.2 1585.75  5635.4 1588.51
#Mann= 3 ,-1 , 0
  3663.6     .05       0    5019     .03       0  5026.3     .05       0
Bank Sta=5019,5026.3
XS Rating Curve= 0 ,0
Exp/Cntr=0.3,0.1

Type RM Length L Ch R = 1 ,14243   ,859,859,859
BEGIN DESCRIPTION:
Deadman 01 26.0
END DESCRIPTION:
XS GIS Cut Line= 3
      1608604.99      6948137.98        1608005.        6947038.
      1607604.97      6946637.97
#Sta/Elev= 30
  3740.6    1587  3808.5 1585.37  3873.9 1585.62  3939.4 1583.14  4042.9 1582.89
  4048.6 1581.73  4070.9 1581.01  4139.3 1581.05  4241.8  1578.2  4309.6 1578.62
  4380.8 1575.92    4397 1576.41  4522.3 1574.21  4560.2 1575.01  4594.9 1573.68
  4720.2 1572.71    4743  1571.4  4756.7 1569.54  4778.6 1571.97  4854.5 1571.31
    4948 1572.21  4997.1 1571.33  5018.2  1568.8  5018.7  1568.3  5025.6  1568.8
    5036 1572.17  5050.1  1572.7  5163.3 1574.58  5318.8 1581.43  5559.3 1586.59
#Mann= 3 ,-1 , 0
  3740.6     .05       0  5018.2     .03       0  5025.6     .05       0
Bank Sta=5018.2,5025.6
XS Rating Curve= 0 ,0
Exp/Cntr=0.3,0.1

Type RM Length L Ch R = 1 ,13384   ,479,479,479
BEGIN DESCRIPTION:
Deadman 01 25.0
END DESCRIPTION:
XS GIS Cut Line= 3
        1608905.        6947488.        1608355.        6946838.
      1607754.99        6946488.
#Sta/Elev= 30
  4153.3 1584.66  4209.9 1582.88  4259.3  1583.1  4295.6 1580.76  4351.6 1580.86
  4387.9 1578.76  4437.3 1578.59  4480.2 1576.18  4593.3  1574.2  4621.9 1572.45
  4692.2  1572.3  4784.5 1569.46  4913.1 1569.95  4933.9 1569.34  4940.5 1567.85
  4948.2 1568.65    4951 1567.07  4951.5 1566.57  4958.6 1567.07  4962.5 1569.96
    4969 1568.52  4991.1 1570.14  5027.9 1567.33  5034.1 1568.82  5055.6 1569.59
  5370.7 1574.53  5450.9 1578.41    5627 1583.44    5670 1586.82  5699.4    1586
#Mann= 3 ,-1 , 0
  4153.3     .05       0    4951     .05       0  4958.6     .05       0
Bank Sta=4951,4958.6
XS Rating Curve= 0 ,0
Exp/Cntr=0.3,0.1

Type RM Length L Ch R = 1 ,12905   ,423,423,423
BEGIN DESCRIPTION:
Deadman 01 24.0
END DESCRIPTION:
XS GIS Cut Line= 3
      1609204.98      6947237.97        1608555.        6946438.
      1607755.04        6946438.
#Sta/Elev= 30
  3969.5 1584.43  4005.4 1583.01  4075.8 1583.09  4125.3 1581.01  4197.2 1580.69
  4225.9 1578.65  4275.5 1578.58  4304.2 1576.85  4353.8 1576.44  4417.7 1574.25
  4473.7 1574.37  4531.2 1572.38  4609.5 1572.53  4679.9 1570.38  4737.3  1570.7
  4807.7 1569.03    4886 1568.27  4922.7 1569.33  4968.3 1567.61  4968.8 1567.11
  4976.2 1567.61  5030.2 1569.34  5050.2 1568.82  5180.2 1570.44  5230.2 1572.41
  5380.2 1574.75  5470.2 1578.43  5720.2 1583.34  5770.2 1586.63  5800.2 1586.69
#Mann= 3 ,-1 , 0
  3969.5     .05       0  4968.3     .05       0  4976.2     .05       0
Bank Sta=4968.3,4976.2
XS Rating Curve= 0 ,0
Exp/Cntr=0.3,0.1

Type RM Length L Ch R = 1 ,12482   ,445,445,445
BEGIN DESCRIPTION:
Deadman 01 23.0
END DESCRIPTION:
XS GIS Cut Line= 3
      1609955.01        6946488.        1608755.        6946088.
      1608255.03      6945688.02
#Sta/Elev= 30
  3730.1 1587.22  3772.3    1585  3930.4 1583.17  3940.9 1581.91    3962 1581.51
  4162.3 1578.28  4267.7 1577.63    4352 1574.53  4457.4 1572.98  4541.8 1570.29
  4626.1 1570.36  4710.4 1568.63  4805.3 1568.98  4942.3 1567.77  4984.5 1568.43
  5008.6 1567.65    5019 1565.14  5019.5 1564.64    5027 1565.14    5031 1568.37
  5037.4 1568.43  5059.1 1567.54  5101.5 1568.06  5229.5 1566.73  5272.8 1567.42
  5287.2 1568.06  5315.2 1577.02  5322.4 1577.62  5528.9 1578.54  5635.3 1583.36
#Mann= 3 ,-1 , 0
  3730.1     .05       0    5019     .05       0    5027     .05       0
Bank Sta=5019,5027
XS Rating Curve= 0 ,0
Exp/Cntr=0.3,0.1

Type RM Length L Ch R = 1 ,12037   ,431,431,431
BEGIN DESCRIPTION:
Deadman 01 22.0
END DESCRIPTION:
XS GIS Cut Line= 3
       1609671.2      6945904.51        1608705.        6945688.
      1608398.46      6945653.84
#Sta/Elev= 30
  4018.3 1578.33  4137.4  1574.2  4198.9 1574.33  4239.9 1572.25    4303 1572.09
  4373.1 1569.92  4433.1 1570.58  4486.7 1568.49  4567.8 1569.14  4573.5 1568.32
  4680.5 1567.57  4834.2 1567.55  4854.7 1568.39    4865 1567.73  4875.2 1565.26
  4885.5 1565.09  4897.5 1566.71  4916.2  1563.6  4926.5 1566.43  4940.9 1567.23
  4984.2 1565.83  4989.3 1564.66  4998.2 1564.91  5001.9 1563.44  5002.4 1562.94
    5010 1563.44  5038.6 1571.64  5053.7 1571.24  5169.5 1576.73  5316.9 1578.81
#Mann= 3 ,-1 , 0
  4018.3     .05       0  5001.9     .05       0    5010     .05       0
Bank Sta=5001.9,5010
XS Rating Curve= 0 ,0
Exp/Cntr=0.3,0.1

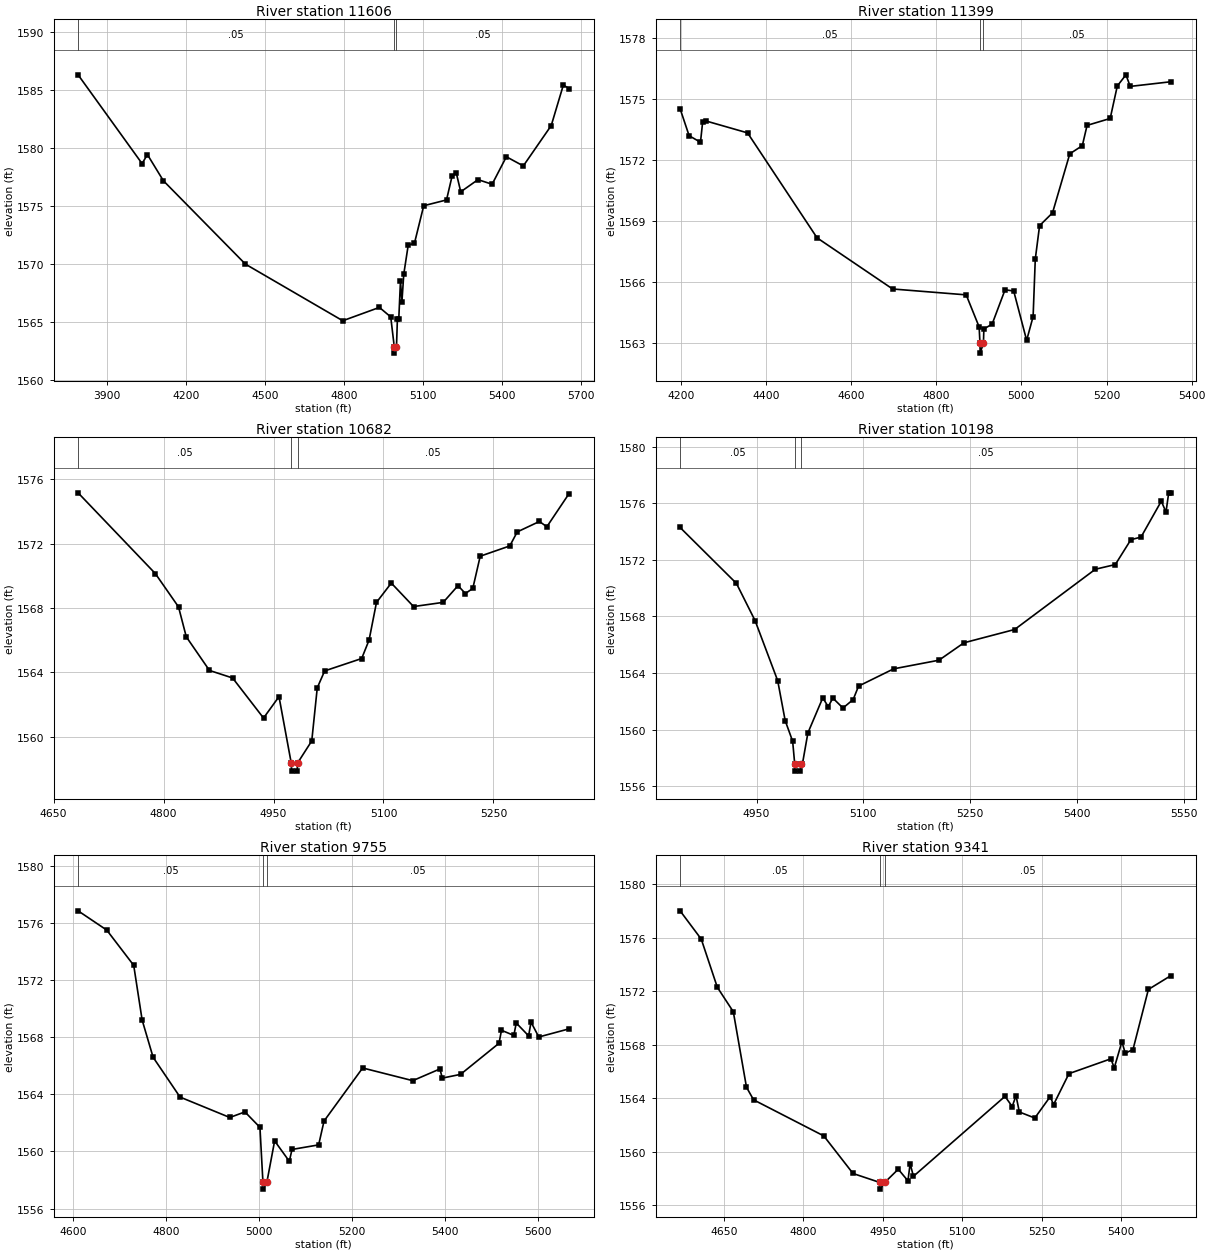
Type RM Length L Ch R = 1 ,11606   ,207,207,207
BEGIN DESCRIPTION:
Deadman 01 21.0
END DESCRIPTION:
XS GIS Cut Line= 3
      1610004.96      6945487.99        1608805.        6945288.
      1608205.01      6945537.99
#Sta/Elev= 30
  3789.2 1586.33  4032.5 1578.68  4052.7 1579.46  4113.6  1577.2  4425.3 1570.02
  4795.4 1565.14  4934.7 1566.29  4977.8 1565.47  4991.5 1562.85    4992 1562.35
  4999.6 1562.85  5003.2 1565.31  5008.4 1565.31  5014.9 1568.59  5020.3 1566.76
  5027.4 1569.16  5044.2 1571.65    5068 1571.82  5103.2 1575.05  5189.9 1575.55
  5211.5 1577.65  5227.3 1577.84    5244 1576.25  5309.6  1577.3  5363.2  1576.9
  5417.4 1579.27  5481.8 1578.48    5588 1581.96    5634 1585.45  5655.7 1585.15
#Mann= 3 ,-1 , 0
  3789.2     .05       0  4991.5     .05       0  4999.6     .05       0
Bank Sta=4991.5,4999.6
XS Rating Curve= 0 ,0
Exp/Cntr=0.3,0.1

Type RM Length L Ch R = 1 ,11399   ,717,717,717
BEGIN DESCRIPTION:
Deadman 01 20.0
END DESCRIPTION:
XS GIS Cut Line= 3
      1609645.89      6945242.01      1609002.66      6945122.22
      1608510.45      6945038.88
#Sta/Elev= 30
  4198.1 1574.53  4219.3  1573.2    4246 1572.88  4251.1 1573.88    4260 1573.92
  4356.6 1573.34  4519.9 1568.17  4697.4 1565.65  4870.3 1565.36  4900.7 1563.78
  4902.6 1562.99  4903.1 1562.49  4910.8 1562.99  4911.8 1563.68  4931.2 1563.92
  4961.6 1565.61  4981.9 1565.55  5012.3 1563.12  5027.5 1564.29  5032.6 1567.12
  5042.7 1568.77  5073.1  1569.4  5113.7 1572.31  5143.1 1572.71  5154.3 1573.71
  5208.6 1574.05  5225.3 1575.65  5245.6  1576.2  5255.7 1575.63  5351.6 1575.86
#Mann= 3 ,-1 , 0
  4198.1     .05       0  4902.6     .05       0  4910.8     .05       0
Bank Sta=4902.6,4910.8
XS Rating Curve= 0 ,0
Exp/Cntr=0.3,0.1

Type RM Length L Ch R = 1 ,10682   ,484,484,484
BEGIN DESCRIPTION:
Deadman 01 19.0
END DESCRIPTION:
XS GIS Cut Line= 3
        1609205.        6944588.        1608905.        6944688.
      1608554.98        6944638.
#Sta/Elev= 30
  4683.4 1575.15  4788.8 1570.13  4820.4 1568.06    4831  1566.2  4862.6 1564.11
  4894.2 1563.64  4936.4 1561.15  4957.5 1562.48  4974.2 1558.35  4974.7 1557.85
  4982.3 1557.85  4982.8 1558.35  5002.2 1559.73  5009.7 1563.03  5019.8 1564.08
  5070.3 1564.85  5080.4    1566  5090.5 1568.34  5110.7 1569.54  5141.1 1568.08
  5181.5 1568.34  5201.7 1569.38  5211.8 1568.89  5221.9 1569.21    5232 1571.21
  5272.4 1571.85  5282.5 1572.72  5312.8 1573.37  5322.9 1573.04  5353.2  1575.1
#Mann= 3 ,-1 , 0
  4683.4     .05       0  4974.2     .05       0  4982.8     .05       0
Bank Sta=4974.2,4982.8
XS Rating Curve= 0 ,0
Exp/Cntr=0.3,0.1

Type RM Length L Ch R = 1 ,10198   ,443,443,443
BEGIN DESCRIPTION:
Deadman 01 18.0
END DESCRIPTION:
XS GIS Cut Line= 3
      1609055.02      6944187.99        1608905.        6944238.
      1608505.03      6944587.97
#Sta/Elev= 30
  4842.6 1574.29  4921.7 1570.34    4948  1567.7  4979.7 1563.46  4990.2 1560.64
  5000.7 1559.18  5003.6 1557.57  5004.1 1557.07  5011.7 1557.07  5012.2 1557.57
  5014.5  1557.6  5022.1 1559.77    5043 1562.25  5050.6 1561.63  5057.2 1562.23
  5071.4 1561.53  5085.7 1562.13  5093.3 1563.08  5142.6  1564.3  5206.2 1564.91
  5241.3 1566.14  5312.5 1567.08  5425.9 1571.34  5453.9 1571.67  5475.8 1573.43
    5490 1573.61  5518.5 1576.15  5525.1 1575.38  5528.9 1576.74  5532.2 1576.74
#Mann= 3 ,-1 , 0
  4842.6     .05       0  5003.6     .05       0  5012.2     .05       0
Bank Sta=5003.6,5012.2
XS Rating Curve= 0 ,0
Exp/Cntr=0.3,0.1

Type RM Length L Ch R = 1 ,9755    ,414,414,414
BEGIN DESCRIPTION:
Deadman 01 17.0
END DESCRIPTION:
XS GIS Cut Line= 3
        1609205.        6944038.        1608855.        6943888.
      1608213.11      6943677.24
#Sta/Elev= 30
  4610.1 1576.86  4671.8 1575.51  4729.8 1573.04  4747.9 1569.21  4771.5  1566.6
  4829.5 1563.81  4936.5 1562.38  4969.1 1562.77  5001.4 1561.69  5007.8 1557.86
  5008.3 1557.36  5016.4 1557.86    5033 1560.74  5064.6 1559.31  5070.4 1560.14
  5127.7 1560.46  5139.3 1562.13  5222.4 1565.85  5330.2 1564.96  5388.6 1565.78
  5393.8 1565.14    5433  1565.4  5515.8 1567.58  5521.1 1568.49  5547.7 1568.13
  5552.9    1569  5579.5  1568.1  5584.7 1569.06  5601.4 1568.02  5666.5 1568.59
#Mann= 3 ,-1 , 0
  4610.1     .05       0  5007.8     .03       0  5016.4     .05       0
Bank Sta=5007.8,5016.4
XS Rating Curve= 0 ,0
Exp/Cntr=0.3,0.1

Type RM Length L Ch R = 1 ,9341    ,496,496,496
BEGIN DESCRIPTION:
Deadman 01 16.0
END DESCRIPTION:
XS GIS Cut Line= 3
      1609304.95      6943737.98        1608905.        6943588.
      1608504.96      6943287.97
#Sta/Elev= 30
    4567 1578.03    4607 1575.91  4637.3 1572.31  4667.5 1570.48  4692.4 1564.83
  4705.8 1563.89  4838.4 1561.19  4893.6 1558.38  4944.1 1557.71  4944.6 1557.21
  4953.5 1557.71    4979  1558.7  4997.3 1557.83  5001.4 1559.11  5007.7 1558.17
  5180.6 1564.15  5194.2 1563.39  5201.4  1564.2  5207.7 1562.98  5236.9 1562.53
    5266 1564.13  5272.3 1563.53  5301.4 1565.85  5380.6 1566.96  5386.9 1566.28
  5401.4 1568.24  5407.7 1567.38  5422.3 1567.65  5451.4 1572.15  5494.2 1573.19
#Mann= 3 ,-1 , 0
    4567     .05       0  4944.1     .03       0  4953.5     .05       0
Bank Sta=4944.1,4953.5
XS Rating Curve= 0 ,0
Exp/Cntr=0.3,0.1

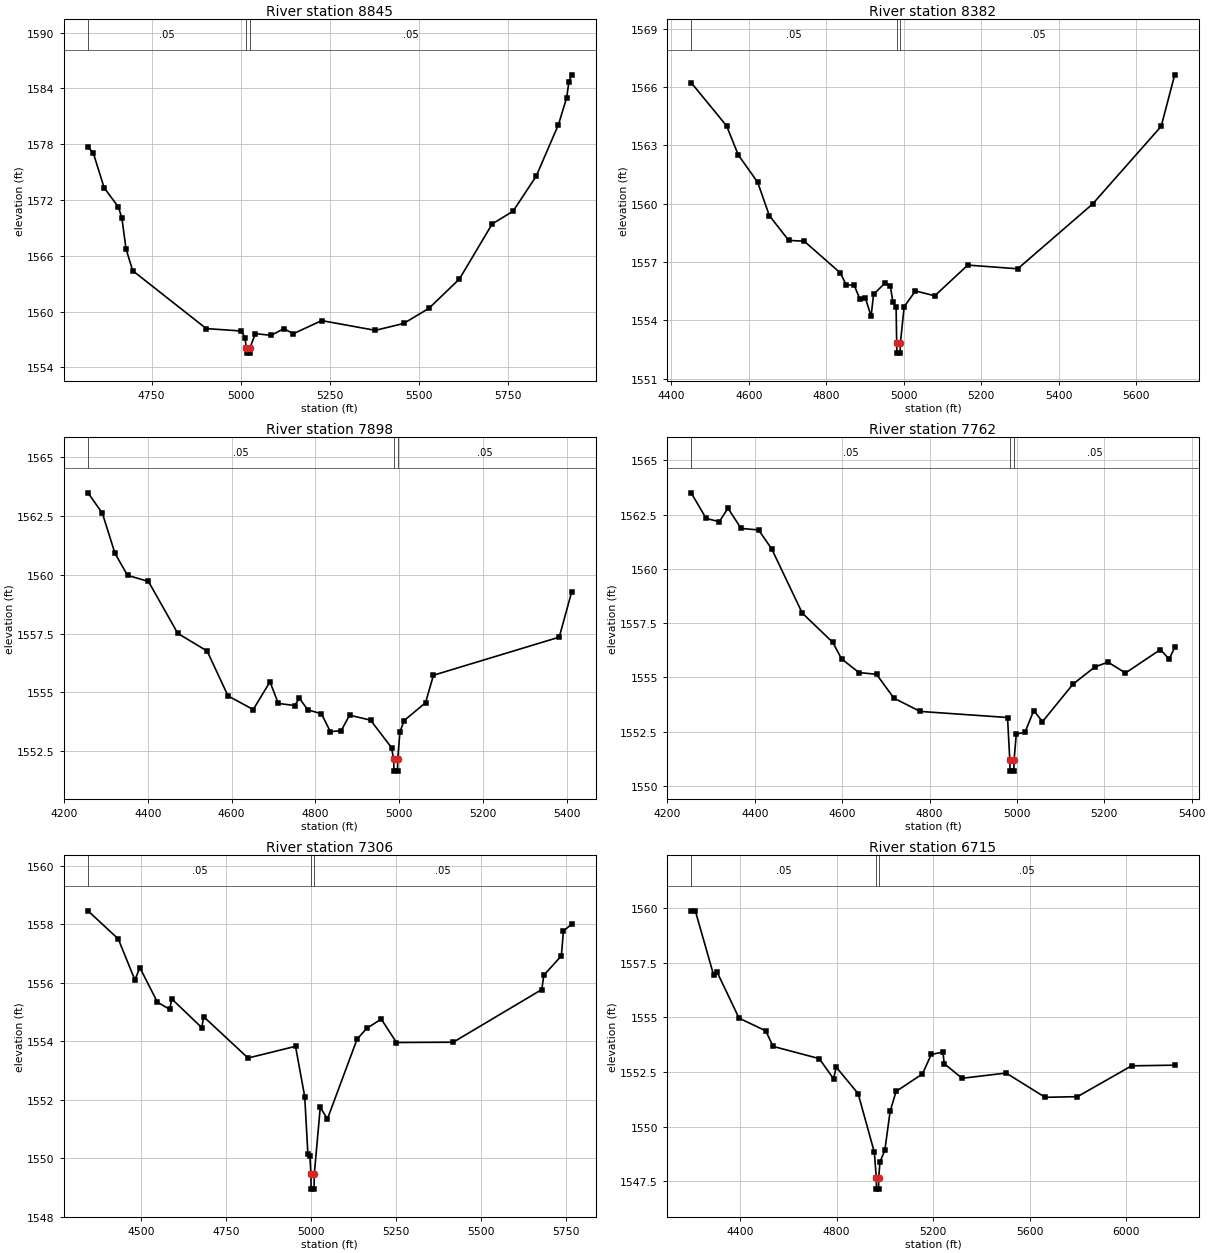
Type RM Length L Ch R = 1 ,8845    ,463,463,463
BEGIN DESCRIPTION:
Deadman 01 15.0
END DESCRIPTION:
XS GIS Cut Line= 3
        1609405.      6943637.99        1609255.        6943238.
      1608505.03      6942688.02
#Sta/Elev= 30
  4571.5 1577.72  4586.6 1577.04  4616.9 1573.32  4656.9 1571.25  4666.7 1570.06
  4678.3 1566.74    4697  1564.4  4903.5 1558.17  5001.8 1557.91  5012.2 1557.21
    5016 1556.03  5016.5 1555.53  5024.9 1555.53  5025.4 1556.03  5041.5 1557.63
  5085.5 1557.44    5121 1558.16  5148.1 1557.62  5227.5 1559.03    5378 1557.98
  5457.5 1558.72  5528.5 1560.35  5614.2 1563.51  5706.1 1569.43  5764.7  1570.8
  5829.5 1574.56  5892.1 1580.12  5915.2 1583.02  5921.4 1584.72  5928.7 1585.47
#Mann= 3 ,-1 , 0
  4571.5     .05       0    5016     .03       0  5025.4     .05       0
Bank Sta=5016,5025.4
XS Rating Curve= 0 ,0
Exp/Cntr=0.3,0.1

Type RM Length L Ch R = 1 ,8382    ,484,484,484
BEGIN DESCRIPTION:
Mapping XS aaeee68b
END DESCRIPTION:
XS GIS Cut Line= 3
      1609604.27      6943349.45      1609590.89      6943018.41
      1609035.73      6942289.33
#Sta/Elev= 30
  4451.4 1566.23  4542.9    1564  4572.9 1562.51    4623  1561.1    4653 1559.39
  4703.1 1558.11  4743.1 1558.07  4836.7 1556.43  4851.3 1555.82  4872.1  1555.8
  4886.6  1555.1  4901.2 1555.13  4915.7 1554.21    4922 1555.33  4951.1 1555.91
  4965.6 1555.74  4971.9 1554.94  4980.2 1554.66  4981.7 1552.81  4982.2 1552.31
  4990.7 1552.31  4991.2 1552.81    5001  1554.7  5030.1 1555.51    5080 1555.26
  5165.2 1556.84  5294.1 1556.65  5487.1 1559.98  5664.2 1563.98  5699.1 1566.63
#Mann= 3 ,-1 , 0
  4451.4     .05       0  4981.7     .03       0  4991.2     .05       0
Bank Sta=4981.7,4991.2
XS Rating Curve= 0 ,0
Exp/Cntr=0.3,0.1

Type RM Length L Ch R = 1 ,7898    ,136,136,136
BEGIN DESCRIPTION:
Mapping XS 731518ab
END DESCRIPTION:
XS GIS Cut Line= 3
      1609620.99      6943232.39      1609631.03      6942677.29
      1609604.27      6942078.68
#Sta/Elev= 30
  4257.1 1563.49  4291.5 1562.62  4321.5 1560.92  4351.5 1559.98  4401.5 1559.72
  4471.5 1557.51  4541.5 1556.76  4591.5 1554.85  4651.6 1554.27  4691.6 1555.45
  4711.6 1554.53    4751 1554.44  4761.6 1554.76  4781.6 1554.26  4814.4 1554.09
  4835.9 1553.33  4861.6 1553.37  4881.7 1554.03  4931.7 1553.82  4981.8 1552.65
    4987 1552.15  4987.5 1551.65  4996.1 1551.65  4996.6 1552.15  5001.8 1553.31
  5011.8  1553.8    5063 1554.56  5081.9 1555.73  5382.2 1557.35  5411.5 1559.25
#Mann= 3 ,-1 , 0
  4257.1     .05       0    4987     .03       0  4996.6     .05       0
Bank Sta=4987,4996.6
XS Rating Curve= 0 ,0
Exp/Cntr=0.3,0.1

Type RM Length L Ch R = 1 ,7762    ,456,456,456
BEGIN DESCRIPTION:
Mapping XS 54ecf7c3
END DESCRIPTION:
XS GIS Cut Line= 2
      1609748.07      6943182.29      1609741.39      6942075.31
#Sta/Elev= 30
  4254.2  1563.5  4288.5 1562.32  4318.5 1562.17  4338.5 1562.79  4368.5 1561.86
  4408.5 1561.79  4438.5 1560.92  4508.5 1557.96  4578.5 1556.61  4598.5 1555.85
  4638.5 1555.22  4678.5 1555.14  4718.5 1554.04  4778.5 1553.43  4978.5 1553.15
  4983.7 1551.18  4984.2 1550.68  4992.9 1550.68  4993.4 1551.18  4998.5 1552.39
  5018.5 1552.47  5038.5 1553.47  5058.5 1552.96  5128.5 1554.69  5178.5 1555.48
  5208.5  1555.7  5248.5  1555.2  5328.5 1556.28  5348.5 1555.84  5361.2 1556.38
#Mann= 3 ,-1 , 0
  4254.2     .05       0  4983.7     .03       0  4993.4     .05       0
Bank Sta=4983.7,4993.4
XS Rating Curve= 0 ,0
Exp/Cntr=0.3,0.1

Type RM Length L Ch R = 1 ,7306    ,591,591,591
BEGIN DESCRIPTION:
Mapping XS 8dfee54a
END DESCRIPTION:
XS GIS Cut Line= 2
      1610460.39      6942744.17      1609694.58      6941546.95
#Sta/Elev= 30
  4344.1 1558.46  4433.1  1557.5    4482  1556.1  4496.6 1556.52  4548.1 1555.34
  4584.5 1555.09  4590.4 1555.45  4678.4 1554.47  4684.3 1554.84  4814.6 1553.43
  4954.1 1553.83  4981.2 1552.11  4990.4 1550.16  4996.4 1550.07  4999.4 1549.45
  4999.9 1548.95  5008.7 1548.95  5009.2 1549.45  5026.8 1551.74    5048 1551.35
  5134.9 1554.07    5163 1554.44  5206.1 1554.76  5250.9 1553.96  5417.5 1553.97
    5678 1555.77  5683.9 1556.26  5735.5 1556.92  5741.5 1557.77  5765.3    1558
#Mann= 3 ,-1 , 0
  4344.1     .05       0  4999.4     .05       0  5009.2     .05       0
Bank Sta=4999.4,5009.2
XS Rating Curve= 0 ,0
Exp/Cntr=0.3,0.1

Type RM Length L Ch R = 1 ,6715    ,560,560,560
BEGIN DESCRIPTION:
Mapping XS 73b80e2d
END DESCRIPTION:
XS GIS Cut Line= 3
      1610731.29      6943005.06       1610634.3      6942202.41
      1610206.23      6941085.42
#Sta/Elev= 30
    4197 1559.84  4214.2 1559.87  4290.4 1556.92  4304.8 1557.06  4395.5 1554.96
  4506.3 1554.38  4536.3 1553.67  4727.9 1553.11  4787.3 1552.19  4798.4 1552.72
  4889.1 1551.51  4956.3 1548.83  4964.7 1547.64  4965.2 1547.14    4974 1547.14
  4974.5 1547.64  4979.7 1548.38  4999.9 1548.92  5021.9  1550.7  5046.6 1551.61
    5156 1552.41  5192.3  1553.3  5240.8 1553.41  5246.1 1552.88  5320.2 1552.21
  5502.8 1552.45  5664.5 1551.34  5798.6 1551.37  6022.9 1552.78  6201.7 1552.81
#Mann= 3 ,-1 , 0
    4197     .05       0  4964.7     .03       0  4974.5     .05       0
Bank Sta=4964.7,4974.5
XS Rating Curve= 0 ,0
Exp/Cntr=0.3,0.1

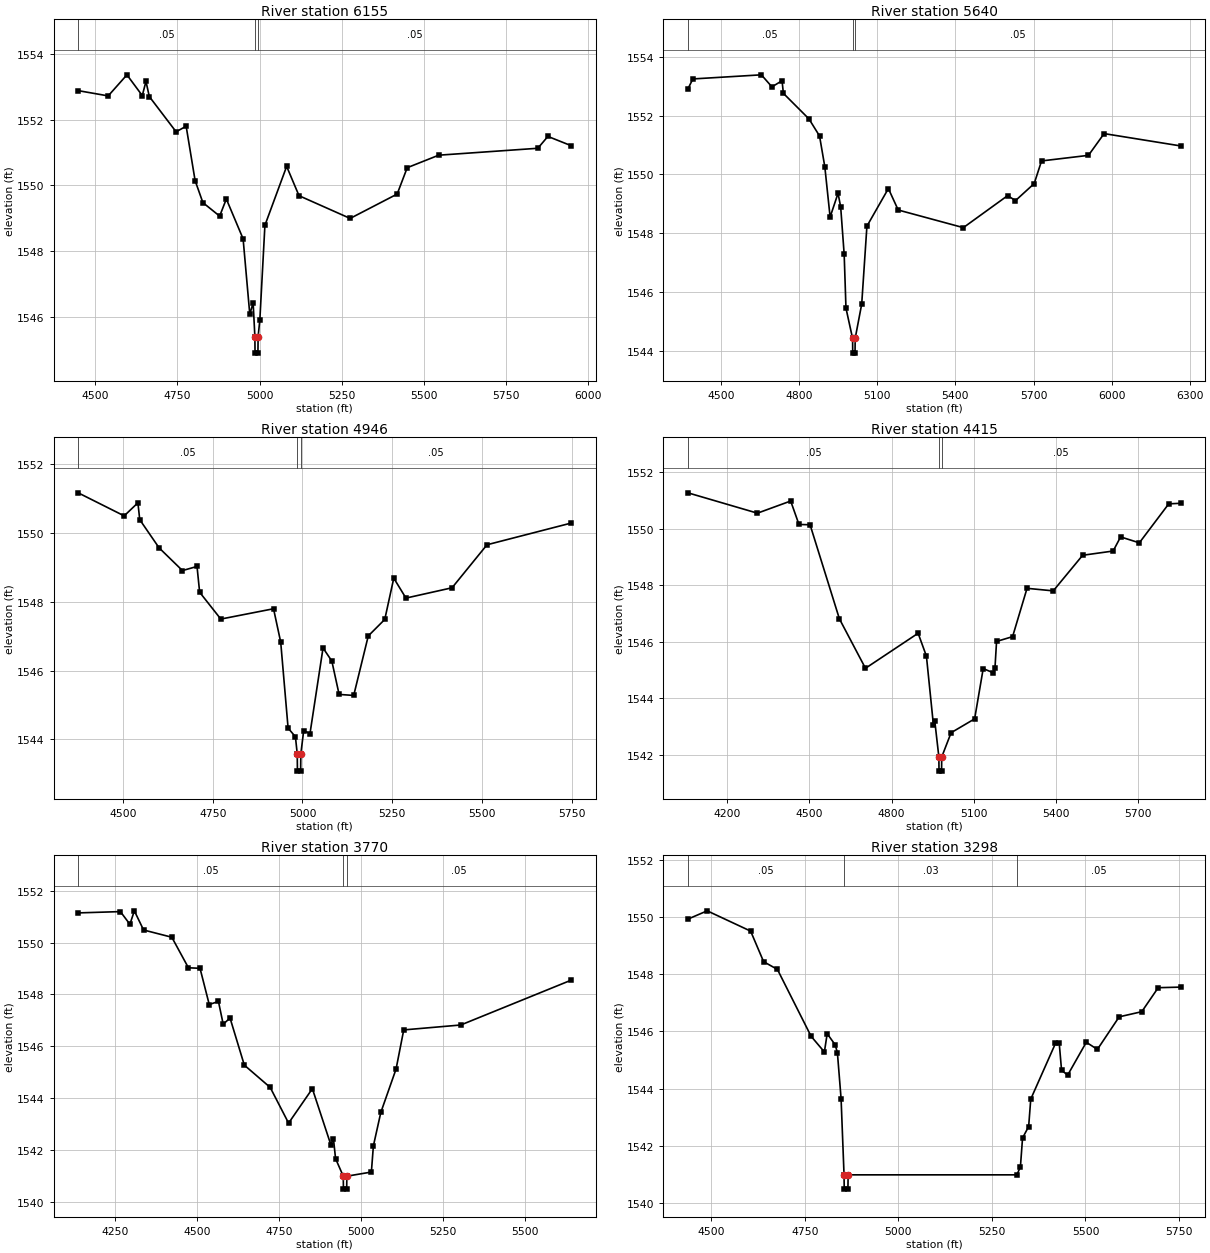
Type RM Length L Ch R = 1 ,6155    ,515,515,515
BEGIN DESCRIPTION:
Mapping XS e2a2623b
END DESCRIPTION:
XS GIS Cut Line= 2
      1611032.26      6942580.36      1611316.52      6941108.86
#Sta/Elev= 30
  4448.4 1552.88  4539.7 1552.72  4596.6 1553.36  4643.3 1552.73  4654.5 1553.16
  4664.7  1552.7  4746.2 1551.63  4776.7  1551.8  4803.9 1550.15  4827.6 1549.48
  4878.6 1549.07  4898.9 1549.59  4949.9 1548.38  4970.2 1546.09  4980.4 1546.44
  4985.7 1545.41  4986.2 1544.91    4995 1544.91  4995.5 1545.41  5000.8 1545.92
  5016.2 1548.79  5082.3 1550.58  5119.9 1549.69  5275.4    1549  5418.4 1549.74
  5448.9 1550.54  5544.7 1550.92  5846.1 1551.13  5876.7 1551.49  5947.1 1551.21
#Mann= 3 ,-1 , 0
  4448.4     .05       0  4985.7     .05       0  4995.5     .05       0
Bank Sta=4985.7,4995.5
XS Rating Curve= 0 ,0
Exp/Cntr=0.3,0.1

Type RM Length L Ch R = 1 ,5640    ,694,694,694
BEGIN DESCRIPTION:
Deadman 01 8.0
END DESCRIPTION:
XS GIS Cut Line= 3
      1611447.46      6942905.86        1611555.        6942288.
      1611600.24      6941023.86
#Sta/Elev= 30
    4373 1552.91    4392 1553.25    4655 1553.39  4695.6 1552.98  4734.4 1553.19
  4739.5 1552.76  4837.7 1551.89  4878.3 1551.31  4898.6 1550.26  4918.9 1548.55
  4949.4 1549.36  4959.5 1548.89  4972.9 1547.28  4979.8 1545.45  5005.2 1544.42
  5005.7 1543.92  5014.6 1543.92  5015.1 1544.42  5040.2 1545.59  5060.2 1548.24
  5142.6 1549.52  5180.3 1548.79  5430.4 1548.19  5600.5 1549.28  5630.6 1549.11
  5702.4 1549.69  5730.6 1550.46  5910.7 1550.65  5970.8 1551.39  6265.1 1550.97
#Mann= 3 ,-1 , 0
    4373     .05       0  5005.2     .05       0  5015.1     .05       0
Bank Sta=5005.2,5015.1
XS Rating Curve= 0 ,0
Exp/Cntr=0.3,0.1

Type RM Length L Ch R = 1 ,4946    ,531,531,531
BEGIN DESCRIPTION:
Mapping XS 0a3e3da0
END DESCRIPTION:
XS GIS Cut Line= 2
      1612269.64       6942754.2      1612029.14      6941401.42
#Sta/Elev= 30
  4374.7 1551.17  4502.9  1550.5  4541.2 1550.88  4546.3 1550.39  4600.3 1549.57
  4665.4 1548.91    4706 1549.03  4713.3 1548.28  4772.3  1547.5  4919.3  1547.8
  4939.3 1546.83  4959.9 1544.33  4980.3 1544.08  4985.4 1543.58  4985.9 1543.08
  4994.9 1543.08  4995.4 1543.58  5003.4 1544.26  5020.9 1544.17  5057.3 1546.66
  5081.8 1546.28  5102.1 1545.31  5142.8 1545.28  5183.4 1547.01  5229.4 1547.49
  5254.5 1548.69  5288.4 1548.11    5417 1548.41  5514.4 1549.66  5748.7 1550.29
#Mann= 3 ,-1 , 0
  4374.7     .05       0  4985.4     .05       0  4995.4     .05       0
Bank Sta=4985.4,4995.4
XS Rating Curve= 0 ,0
Exp/Cntr=0.3,0.1

Type RM Length L Ch R = 1 ,4415    ,645,645,645
BEGIN DESCRIPTION:
Deadman 01 7.0
END DESCRIPTION:
XS GIS Cut Line= 3
      1612489.13      6942898.89      1612627.66      6941960.76
      1612195.38      6941229.01
#Sta/Elev= 30
  4056.6 1551.27  4310.2 1550.55  4431.5 1550.98  4461.8 1550.15  4502.3 1550.14
  4609.3 1546.81  4704.4 1545.06  4896.5  1546.3  4926.8 1545.49  4952.3 1543.06
  4957.3 1543.19  4972.2 1541.92  4972.7 1541.42  4982.1 1541.42  4982.6 1541.92
  5016.9 1542.78  5102.7 1543.27    5134 1545.05  5170.7  1544.9  5176.9 1545.07
  5182.7 1546.01  5241.2 1546.18  5293.9 1547.89  5389.5  1547.8  5496.8 1549.06
    5608 1549.21  5635.3 1549.71  5703.6  1549.5  5810.9 1550.88  5854.8  1550.9
#Mann= 3 ,-1 , 0
  4056.6     .05       0  4972.2     .03       0  4982.6     .05       0
Bank Sta=4972.2,4982.6
XS Rating Curve= 0 ,0
Exp/Cntr=0.3,0.1

Type RM Length L Ch R = 1 ,3770    ,472,472,472
BEGIN DESCRIPTION:
Deadman 01 6.0
END DESCRIPTION:
XS GIS Cut Line= 3
      1612579.99      6942913.02        1613105.        6942238.
      1613367.22        6941648.
#Sta/Elev= 30
  4138.4 1551.15  4266.9  1551.2  4295.9 1550.71  4309.4 1551.23  4337.5 1550.49
  4423.5 1550.21  4474.1 1549.03  4509.4 1549.01  4537.5 1547.61  4565.5 1547.73
    4580 1546.85  4600.8 1547.09  4644.3 1545.27    4723 1544.41  4779.1 1543.03
  4851.5 1544.36  4907.6  1542.2  4915.7 1542.43  4922.1 1541.66  4945.6 1540.98
  4946.1 1540.48    4956 1540.48  4956.5 1540.98  5031.2 1541.14  5037.3 1542.15
  5059.9 1543.44  5106.4 1545.12  5129.7 1546.63  5303.4 1546.82  5639.2 1548.55
#Mann= 3 ,-1 , 0
  4138.4     .05       0  4945.6     .05       0  4956.5     .05       0
Bank Sta=4945.6,4956.5
XS Rating Curve= 0 ,0
Exp/Cntr=0.3,0.1

Type RM Length L Ch R = 1 ,3298    ,252,252,252
BEGIN DESCRIPTION:
Deadman 01 5.0
END DESCRIPTION:
XS GIS Cut Line= 3
      1613121.09      6943072.47        1613405.        6942588.
       1613759.1      6941921.34
#Sta/Elev= 30
  4438.1 1549.93  4489.6 1550.22  4605.6 1549.51  4640.3 1548.44  4677.1 1548.17
  4767.1 1545.83  4802.6 1545.28  4810.1 1545.92  4831.5 1545.53  4837.4 1545.25
  4847.2 1543.65  4855.1 1540.98  4855.6 1540.48  4865.5 1540.48    4866 1540.98
  5316.7 1540.98  5326.2 1541.26  5331.9 1542.27  5348.2 1542.67  5353.8 1543.63
  5419.8 1545.58  5429.9 1545.58  5436.1 1544.64  5452.4 1544.47  5502.1 1545.62
  5531.8 1545.37    5590 1546.51  5650.3 1546.69  5694.2 1547.53  5754.5 1547.55
#Mann= 3 ,-1 , 0
  4438.1     .05       0  4855.1     .03       0  5316.7     .05       0
Bank Sta=4855.1,4866
XS Rating Curve= 0 ,0
Exp/Cntr=0.3,0.1