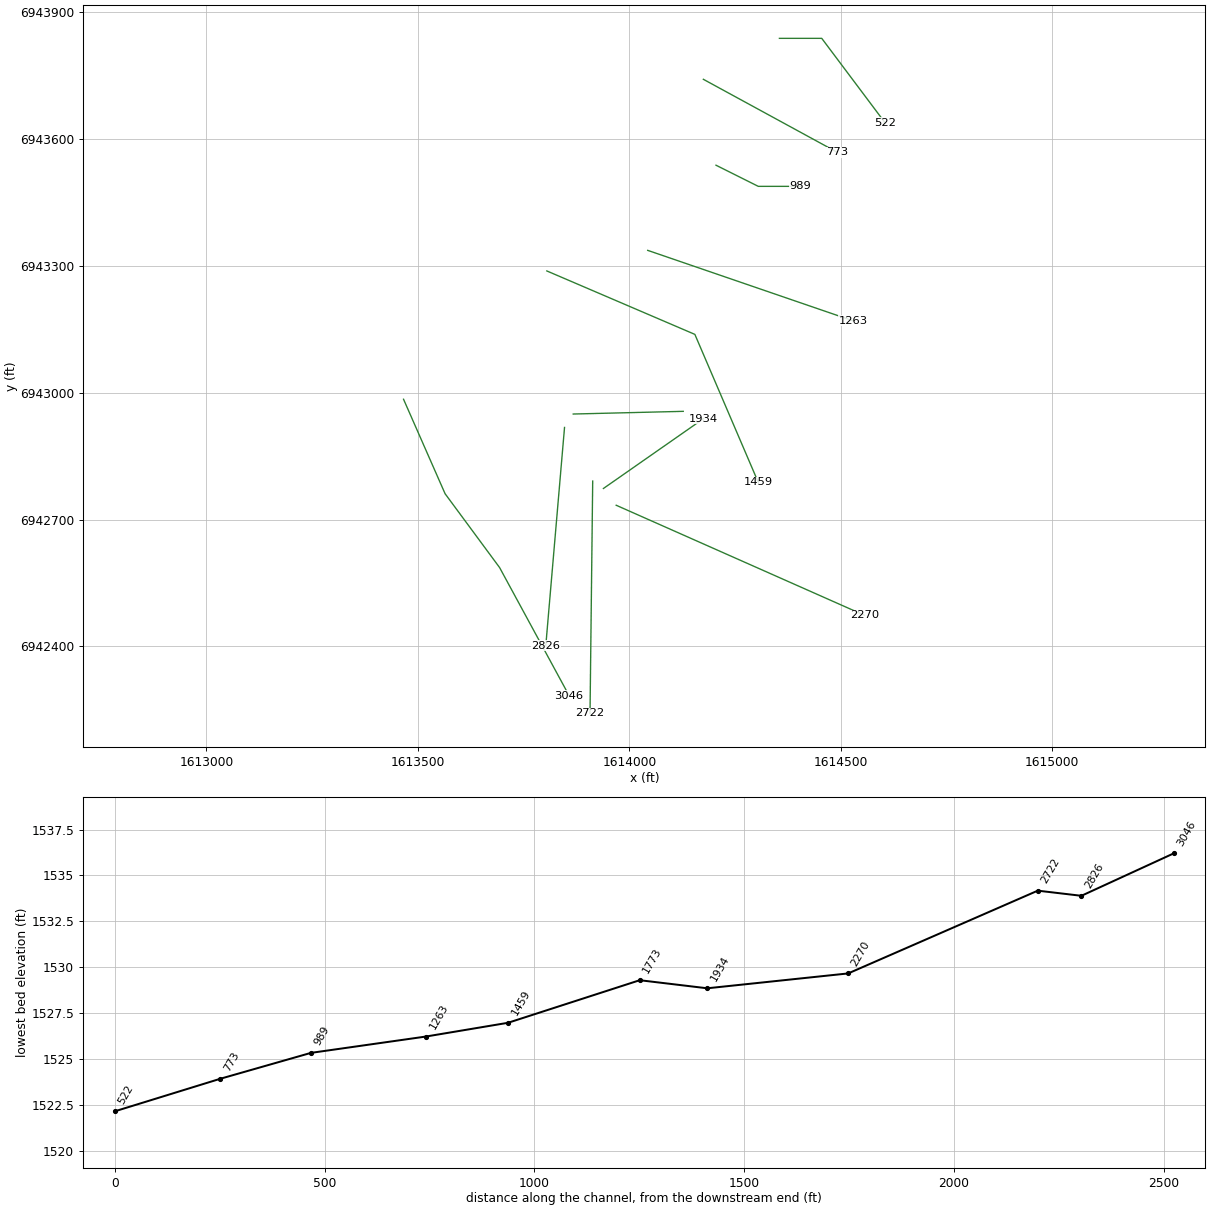
HEC-RAS study Deadman 01.prj: Deadman 01 Base Level Engineering

--- Deadman 01.g01 (geometry) --- (continued)

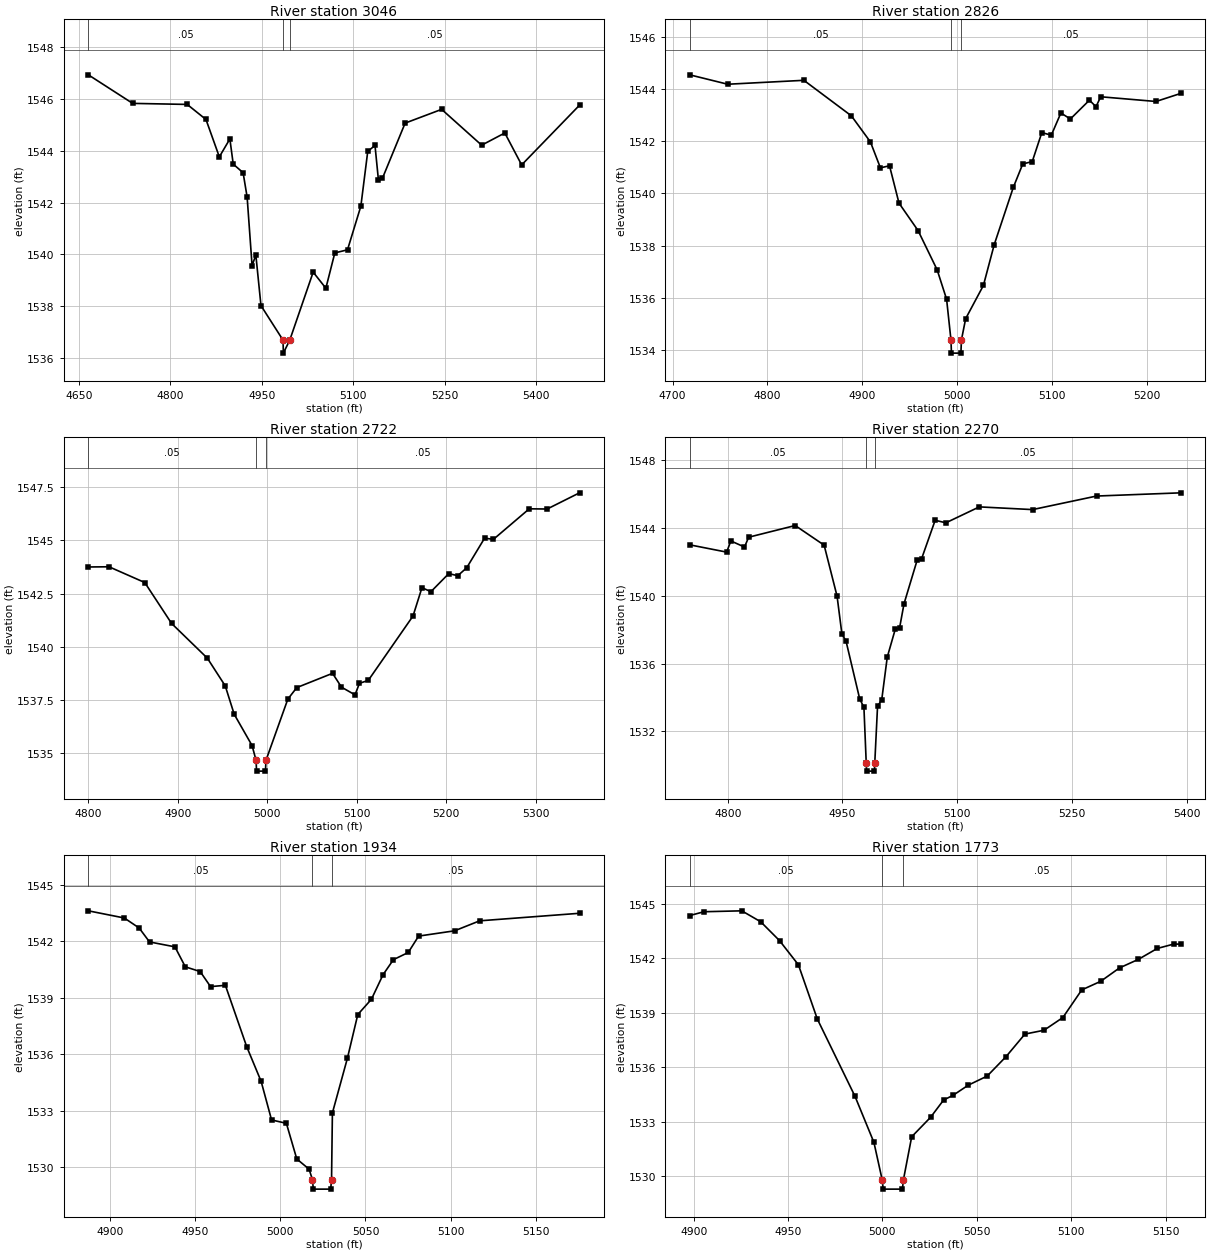
Type RM Length L Ch R = 1 ,3046    ,220,220,220
BEGIN DESCRIPTION:
Mapping XS afea055f
END DESCRIPTION:
XS GIS Cut Line= 4
      1613466.17      6942984.58       1613564.4      6942761.23
      1613693.27      6942586.65      1613857.65      6942283.88
#Sta/Elev= 30
  4665.5 1546.92  4738.2 1545.82  4827.6 1545.78  4858.4  1545.2  4880.3 1543.76
  4897.6 1544.45  4903.1 1543.48  4919.3 1543.15  4925.9 1542.21    4934 1539.57
  4940.2 1539.98  4948.6 1538.03  4984.8  1536.7  4985.3  1536.2  4995.8  1536.7
  5034.2 1539.32    5055  1538.7  5069.7 1540.06  5090.5 1540.18  5112.4 1541.86
  5123.7 1543.97  5135.6  1544.2  5141.3 1542.85  5147.7 1542.93    5185 1545.06
  5244.9 1545.59  5310.5 1544.21  5348.5 1544.68  5376.1 1543.45    5471 1545.75
#Mann= 3 ,-1 , 0
  4665.5     .05       0  4984.8     .03       0  4995.8     .05       0
Bank Sta=4984.8,4995.8
XS Rating Curve= 0 ,0
Exp/Cntr=0.3,0.1

Type RM Length L Ch R = 1 ,2826    ,104,104,104
BEGIN DESCRIPTION:
Mapping XS 75b87b54
END DESCRIPTION:
XS GIS Cut Line= 2
      1613846.82      6942917.92       1613802.5      6942401.92
#Sta/Elev= 30
  4718.1 1544.54  4758.2 1544.18  4838.5 1544.33  4888.6 1542.97  4908.7 1541.97
  4919.2 1540.98  4928.8 1541.06  4938.8 1539.63  4958.9 1538.58    4979 1537.08
    4989 1535.95  4993.6 1534.39  4994.1 1533.89  5004.1 1533.89  5004.6 1534.39
  5009.1 1535.21  5027.8 1536.48  5039.2 1538.04  5059.3 1540.23  5069.3 1541.13
  5079.3 1541.22  5089.4 1542.33  5099.4 1542.23  5109.5 1543.08  5119.5 1542.85
  5139.6 1543.57  5146.5 1543.32  5151.5  1543.7  5209.8 1543.52    5236 1543.83
#Mann= 3 ,-1 , 0
  4718.1     .05       0  4993.6     .05       0  5004.6     .05       0
Bank Sta=4993.6,5004.6
XS Rating Curve= 0 ,0
Exp/Cntr=0.3,0.1

Type RM Length L Ch R = 1 ,2722    ,452,452,452
BEGIN DESCRIPTION:
Mapping XS ce06b57b
END DESCRIPTION:
XS GIS Cut Line= 2
      1613913.44      6942791.11      1613907.11      6942241.85
#Sta/Elev= 30
  4799.9 1543.75    4823 1543.76    4863 1543.02    4893  1541.1    4933 1539.47
    4953 1538.17    4963 1536.84    4983 1535.37  4987.5 1534.67    4988 1534.17
    4998 1534.17  4998.5 1534.67    5023 1537.55    5033 1538.09    5073 1538.76
    5083 1538.11  5098.1 1537.75  5103.1 1538.29    5113 1538.43    5163 1541.45
    5173 1542.78    5183 1542.59    5203 1543.44    5213 1543.34    5223 1543.71
    5243  1545.1    5253 1545.05    5293 1546.48    5313 1546.47  5349.2 1547.23
#Mann= 3 ,-1 , 0
  4799.9     .05       0  4987.5     .05       0  4998.5     .05       0
Bank Sta=4987.5,4998.5
XS Rating Curve= 0 ,0
Exp/Cntr=0.3,0.1

Type RM Length L Ch R = 1 ,2270    ,336,336,336
BEGIN DESCRIPTION:
Mapping XS 26816fe5
END DESCRIPTION:
XS GIS Cut Line= 2
      1613968.95      6942733.98      1614555.78      6942473.87
#Sta/Elev= 30
  4750.3 1543.02  4798.6 1542.59  4804.1 1543.25  4821.9 1542.89  4827.4 1543.47
  4888.2 1544.16    4926    1543  4942.9 1539.99  4949.2 1537.77  4954.7 1537.32
  4972.5 1533.92    4978 1533.43    4981 1530.16  4981.5 1529.66  4991.7 1529.66
  4992.2 1530.16  4995.8 1533.48  5001.3 1533.88  5008.5 1536.39  5019.1 1538.06
  5024.5 1538.09  5030.4 1539.54  5047.8 1542.15  5053.3 1542.19  5071.1 1544.47
  5085.1 1544.32  5128.8 1545.26  5198.4  1545.1    5282  1545.9  5392.2 1546.09
#Mann= 3 ,-1 , 0
  4750.3     .05       0    4981     .05       0  4992.2     .05       0
Bank Sta=4981,4992.2
XS Rating Curve= 0 ,0
Exp/Cntr=0.3,0.1

Type RM Length L Ch R = 1 ,1934    ,161,161,161
BEGIN DESCRIPTION:
Mapping XS 35656974
END DESCRIPTION:
XS GIS Cut Line= 2
      1613938.82      6942773.63      1614175.14      6942938.58
#Sta/Elev= 30
  4887.4 1543.61  4908.5 1543.23  4917.2  1542.7  4923.3 1541.96  4938.2  1541.7
  4944.3 1540.64    4953 1540.39  4959.1 1539.59  4967.8 1539.66  4980.3 1536.41
  4988.8 1534.56  4994.9 1532.52  5003.6 1532.34  5009.7 1530.45  5016.9 1529.91
  5018.9 1529.35  5019.4 1528.85  5029.6 1528.85  5030.1 1529.35  5030.6 1532.89
  5039.4 1535.79  5045.5 1538.11  5053.5 1538.92  5060.3 1540.22  5066.4 1541.02
  5075.1  1541.4  5081.2 1542.27  5102.3 1542.55    5117 1543.08  5175.6 1543.48
#Mann= 3 ,-1 , 0
  4887.4     .05       0  5018.9     .05       0  5030.1     .05       0
Bank Sta=5018.9,5030.1
XS Rating Curve= 0 ,0
Exp/Cntr=0.3,0.1

Type RM Length L Ch R = 1 ,1773    ,314,314,314
BEGIN DESCRIPTION:
Mapping XS 0bb7378a
END DESCRIPTION:
XS GIS Cut Line= 2
      1613867.41      6942949.68      1614127.53      6942956.02
#Sta/Elev= 30
  4897.9 1544.34  4905.5 1544.55  4925.5  1544.6  4935.5    1544  4945.5 1542.96
  4955.5 1541.63  4965.5 1538.65  4985.5 1534.39  4995.5 1531.86  4999.9 1529.79
  5000.4 1529.29  5010.6 1529.29  5011.1 1529.79  5015.5 1532.17  5025.5 1533.24
  5032.4 1534.19  5037.4 1534.45  5045.5 1535.01  5055.5 1535.51  5065.5 1536.58
  5075.5 1537.82  5085.6 1538.03  5095.6 1538.73  5105.6 1540.25  5115.6 1540.72
  5125.6 1541.46  5135.6 1541.93  5145.6 1542.53  5154.3 1542.77  5158.1 1542.77
#Mann= 3 ,-1 , 0
  4897.9     .05       0  4999.9     .05       0  5011.1     .05       0
Bank Sta=4999.9,5011.1
XS Rating Curve= 0 ,0
Exp/Cntr=0.3,0.1

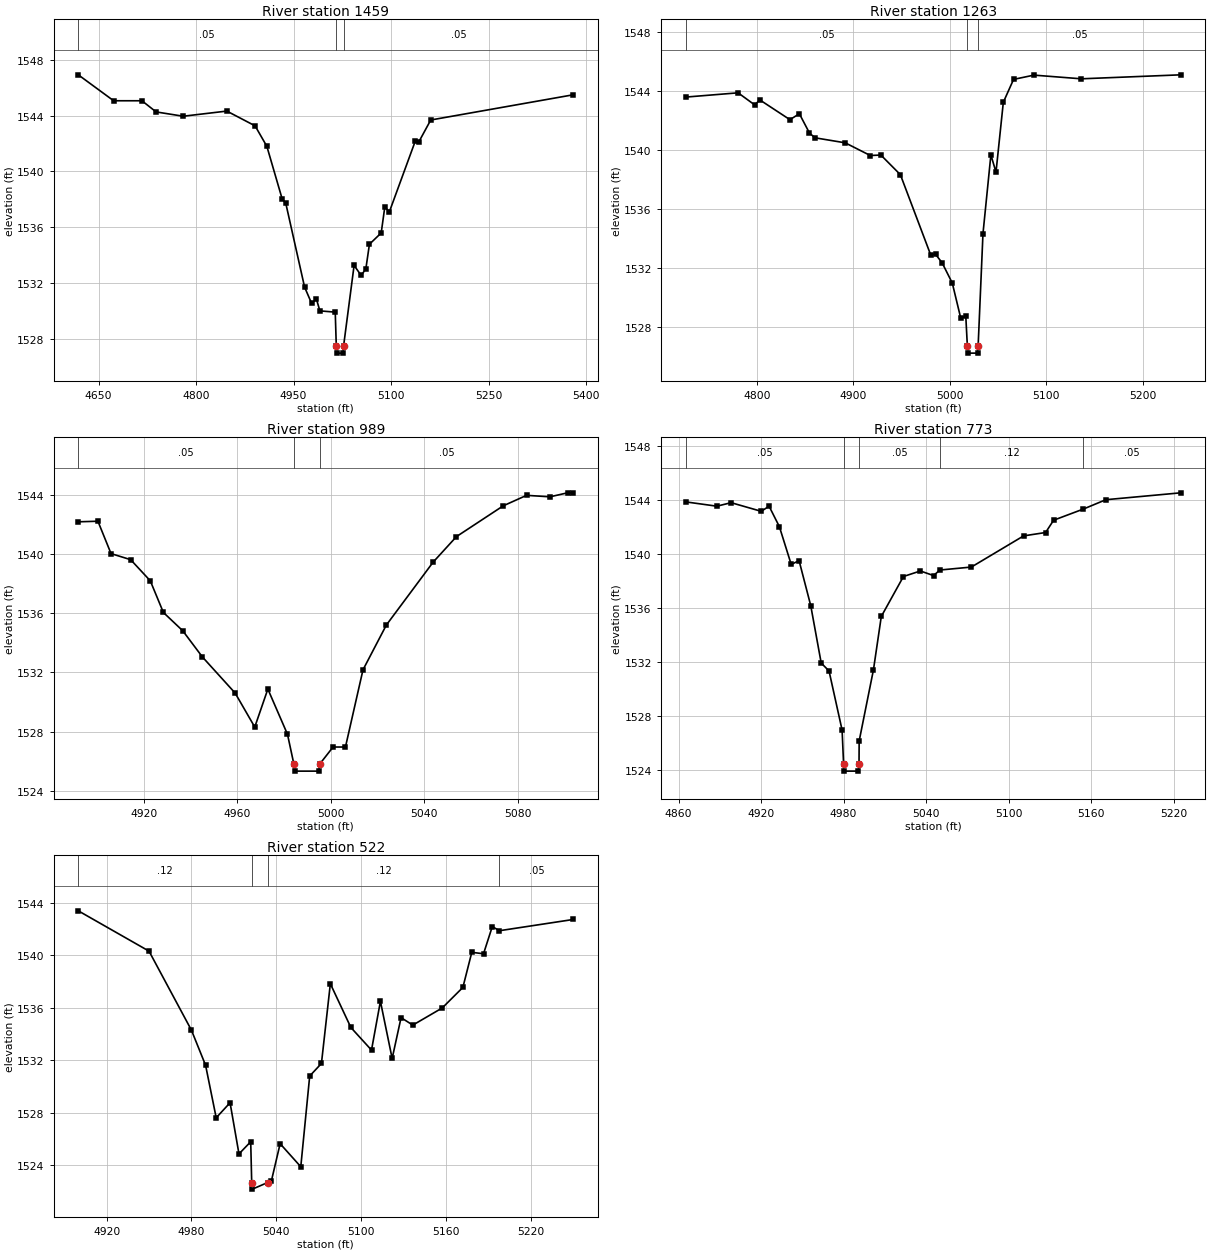
Type RM Length L Ch R = 1 ,1459    ,196,196,196
BEGIN DESCRIPTION:
Deadman 01 3.0
END DESCRIPTION:
XS GIS Cut Line= 3
        1613805.        6943288.        1614155.        6943138.
      1614305.01      6942787.98
#Sta/Elev= 30
  4618.9 1546.93  4673.3 1545.07  4716.8 1545.07  4738.6 1544.27  4780.3 1543.96
  4847.4 1544.33  4890.9 1543.27    4909  1541.8  4932.6 1538.02    4938 1537.74
    4967 1531.71  4977.9 1530.53  4985.2 1530.85  4990.6    1530  5014.2 1529.91
  5015.8 1527.47  5016.3 1526.97  5026.5 1526.97    5027 1527.47  5043.2 1533.26
  5054.1 1532.54  5061.3 1533.02  5066.8 1534.78  5084.9 1535.59  5090.4 1537.44
  5097.6 1537.12  5137.5  1542.2  5142.9 1542.13  5161.1 1543.69  5380.5  1545.5
#Mann= 3 ,-1 , 0
  4618.9     .05       0  5015.8     .05       0    5027     .05       0
Bank Sta=5015.8,5027
XS Rating Curve= 0 ,0
Exp/Cntr=0.3,0.1

Type RM Length L Ch R = 1 ,1263    ,274,274,274
BEGIN DESCRIPTION:
Mapping XS 17250d19
END DESCRIPTION:
XS GIS Cut Line= 2
      1614043.52      6943336.66      1614528.84      6943170.13
#Sta/Elev= 30
  4726.1 1543.58  4780.5 1543.87  4797.7 1543.05    4803 1543.39  4834.2 1542.05
    4844 1542.45  4854.5 1541.14  4860.2 1540.82  4891.5 1540.48  4917.5 1539.62
  4928.5 1539.65  4948.7 1538.32    4980  1532.9  4985.3 1532.91    4992 1532.34
  5002.5 1530.97  5011.3 1528.58  5016.5 1528.72  5018.1 1526.72  5018.6 1526.22
  5028.8 1526.22  5029.3 1526.72  5034.3 1534.32  5042.5 1539.66  5047.8 1538.49
  5055.4 1543.23    5066 1544.78  5087.1 1545.07  5136.3 1544.82  5239.2 1545.09
#Mann= 3 ,-1 , 0
  4726.1     .05       0  5018.1     .05       0  5029.3     .05       0
Bank Sta=5018.1,5029.3
XS Rating Curve= 0 ,0
Exp/Cntr=0.3,0.1

Type RM Length L Ch R = 1 ,989     ,216,216,216
BEGIN DESCRIPTION:
Deadman 01 2.0
END DESCRIPTION:
XS GIS Cut Line= 3
      1614204.98      6943538.01        1614305.        6943488.
      1614404.98        6943488.
#Sta/Elev= 27
    4892 1542.19  4900.4 1542.23    4906 1540.04  4914.4 1539.63  4922.8  1538.2
  4928.4 1536.06  4936.7 1534.82  4945.1 1533.05  4959.1 1530.61  4967.5 1528.31
  4973.1 1530.88  4981.5 1527.82  4984.2 1525.83  4984.7 1525.33  4994.9 1525.33
  4995.4 1525.83    5001 1526.96  5006.3 1526.96  5013.8 1532.18  5023.8 1535.21
  5043.8 1539.46  5053.8 1541.19  5073.8 1543.27  5083.8 1543.98  5093.8 1543.88
  5101.3 1544.15  5103.8 1544.15
#Mann= 3 ,-1 , 0
    4892     .05       0  4984.2     .05       0  4995.4     .05       0
Bank Sta=4984.2,4995.4
XS Rating Curve= 0 ,0
Exp/Cntr=0.3,0.1

Type RM Length L Ch R = 1 ,773     ,251,251,251
BEGIN DESCRIPTION:
Mapping XS 1320ecfe
END DESCRIPTION:
XS GIS Cut Line= 2
       1614175.1      6943741.13       1614491.2      6943568.85
#Sta/Elev= 30
  4865.1 1543.87  4887.8 1543.55  4898.2 1543.81  4920.1 1543.17  4925.8 1543.55
  4933.3 1542.03  4941.9 1539.23  4947.6 1539.52  4956.1 1536.18  4963.7 1531.93
  4969.4 1531.34  4978.9 1526.96    4980 1524.42  4980.5 1523.92  4990.7 1523.92
  4991.2 1524.42  4991.3 1526.15  5001.7 1531.43  5007.4 1535.38  5023.5 1538.34
  5035.8 1538.75  5045.4 1538.41    5050 1538.82  5072.9 1539.04  5110.9 1541.35
  5126.9  1541.6  5132.7 1542.51  5154.4 1543.34  5170.7 1544.03  5225.1 1544.54
#Mann= 5 ,-1 , 0
  4865.1     .05       0    4980     .05       0  4991.2     .05       0
    5050     .12       0  5154.4     .05       0
Bank Sta=4980,4991.2
XS Rating Curve= 0 ,0
Exp/Cntr=0.3,0.1

Type RM Length L Ch R = 1 ,522     ,0,0,0
BEGIN DESCRIPTION:
Deadman 01 1.0
END DESCRIPTION:
XS GIS Cut Line= 3
      1614354.96        6943838.        1614455.        6943838.
      1614604.98      6943638.03
#Sta/Elev= 30
    4900 1543.41    4950 1540.33    4980 1534.29    4990 1531.61  4997.5  1527.6
  5007.3 1528.75  5013.6 1524.84  5021.9 1525.77  5022.6 1522.65  5023.1 1522.15
  5033.8 1522.65  5036.5 1522.77  5042.7 1525.62  5057.3 1523.86  5063.6 1530.79
  5071.9 1531.75  5078.2 1537.84  5092.7  1534.5  5107.3 1532.77  5113.6  1536.5
  5121.9 1532.13  5128.2 1535.25  5136.5 1534.68  5157.3 1535.99  5171.9 1537.56
  5178.2 1540.24  5186.5 1540.13  5192.7 1542.21  5197.7 1541.89    5250 1542.75
#Mann= 4 ,-1 , 0
    4900     .12       0  5022.6     .07       0  5033.8     .12       0
  5197.7     .05       0
Bank Sta=5022.6,5033.8
XS Rating Curve= 0 ,0
Exp/Cntr=0.3,0.1

Chan Stop Cuts=-1
Use User Specified Reach Order=0
Composite Channel Slope=5