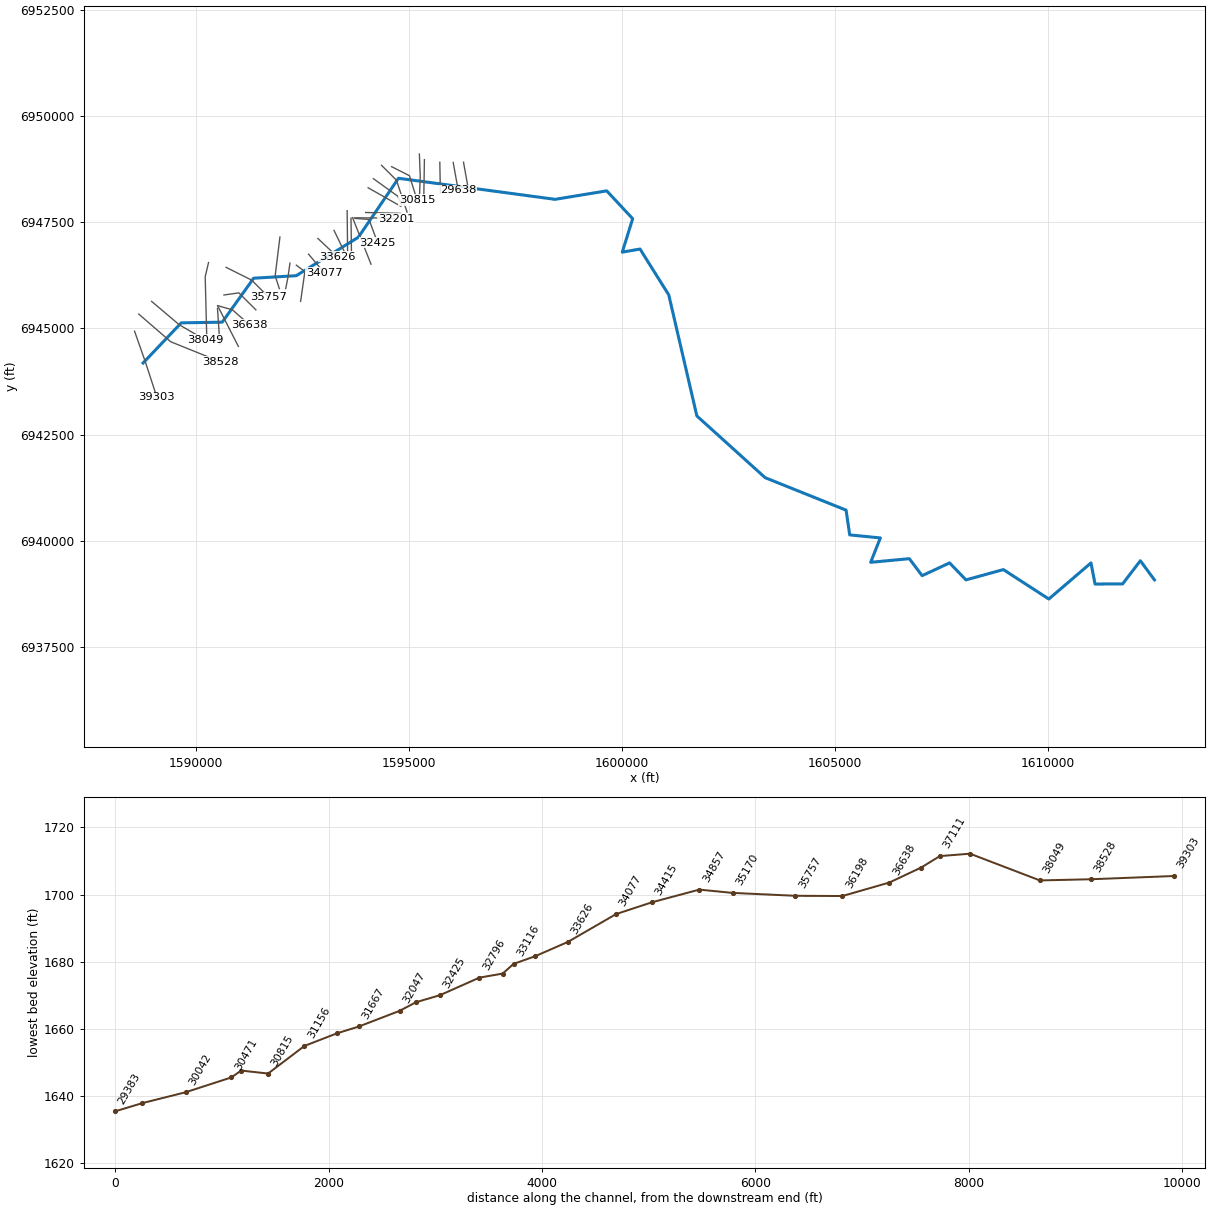
--- Deadman 02.prj (project) ---

Proj Title=Deadman 02 Base Level Engineering
Current Plan=p01
Default Exp/Contr=0.3,0.1
English Units
Geom File=g01
Flow File=f01
Plan File=p01
Y Axis Title=Elevation
X Axis Title(PF)=Main Channel Distance
X Axis Title(XS)=Station
BEGIN DESCRIPTION:
Deadman 02
END DESCRIPTION:
DSS Export Rating Curves= 0
DSS Export Rating Curve Sorted= 0
DSS Export Volume Flow Curves= 0
DXF OffsetX= 0
DXF OffsetY= 0
DXF ScaleX= 1
DXF ScaleY= 10

--- Deadman 02.p01 (plan) ---

Plan Title=Multiple Run
Short Identifier=Multiple
Geom File=g01
Flow File=f01
Subcritical Flow
K Sum by GR= 0
Std Step Tol= 0.01
Critical Tol= 0.01
Num of Std Step Trials= 20
Max Error Tol= 0.3
Flow Tol Ratio= 0.001
Split Flow NTrial= 30
Split Flow Tol= 0.02
Split Flow Ratio= 0.02
Log Output Level= 0
Friction Slope Method= 1
Unsteady Friction Slope Method= 2
Unsteady Bridges Friction Slope Method= 1
Parabolic Critical Depth
Global Vel Dist=  1 , 1 , 1
Global Log Level= 0
CheckData=True
Encroach Param= -1, 0, 0, 0
BEGIN DESCRIPTION:
Multiple Run
END DESCRIPTION:

--- Deadman 02.f01 (steady flow) ---

Flow Title=Multiple
Number of Profiles=7
Profile Names=10-year,25-year,50-year,1pct_min,100-year,1pct_plu,500-year
River Rch & RM= Deadman 02,Reach-1,39303
     327     453     556     340     678    1353    1020
River Rch & RM= Deadman 02,Reach-1,28028
     408     573     711     438     874    1744    1339
River Rch & RM= Deadman 02,Reach-1,26082
     485     687     857     532    1061    2116    1645
River Rch & RM= Deadman 02,Reach-1,21926
     552     787     986     613    1224    2442    1911
River Rch & RM= Deadman 02,Reach-1,18269
     583     833    1045     651    1298    2591    2033
River Rch & RM= Deadman 02,Reach-1,17163
     763    1103    1396     877    1749    3490    2782
River Rch & RM= Deadman 02,Reach-1,12807
     831    1206    1530     962    1919    3830    3063
River Rch & RM= Deadman 02,Reach-1,9403
     889    1293    1642    1034    2063    4117    3302
River Rch & RM= Deadman 02,Reach-1,2954
     900    1308    1661    1046    2086    4163    3336
Boundary for River Rch & Prof#=Deadman 02,Reach-1,1
Up Type=0
Dn Type=3
Dn Slope=0.009
Boundary for River Rch & Prof#=Deadman 02,Reach-1,2
Up Type=0
Dn Type=3
Dn Slope=0.009
Boundary for River Rch & Prof#=Deadman 02,Reach-1,3
Up Type=0
Dn Type=3
Dn Slope=0.009
Boundary for River Rch & Prof#=Deadman 02,Reach-1,4
Up Type=0
Dn Type=3
Dn Slope=0.009
Boundary for River Rch & Prof#=Deadman 02,Reach-1,5
Up Type=0
Dn Type=3
Dn Slope=0.009
Boundary for River Rch & Prof#=Deadman 02,Reach-1,6
Up Type=0
Dn Type=3
Dn Slope=0.009
Boundary for River Rch & Prof#=Deadman 02,Reach-1,7
Up Type=0
Dn Type=3
Dn Slope=0.009

--- Deadman 02.g01 (geometry) ---

Geom Title=Existing Conditions
Program Version=4.10

River Reach=Deadman 02      ,Reach-1
Reach XY= 30
        1588755.        6944188.      1589652.26      6945132.66
       1590614.8      6945148.48      1591352.55      6946182.53
      1592353.42      6946241.83      1593811.19      6947145.82
      1594752.55      6948532.54      1598430.18      6948037.54
      1599643.28      6948236.95        1600253.      6947582.31
      1600008.46      6946795.74      1600425.17      6946868.44
      1601100.03      6945790.58      1601760.44      6942943.25
      1603363.48      6941491.51      1605264.66      6940727.83
      1605348.86      6940145.73      1606068.83      6940074.67
      1605841.26      6939501.19      1606749.37      6939586.39
      1607049.99      6939187.12      1607694.36      6939487.45
      1608079.88      6939087.68      1608958.29      6939329.95
      1610025.21      6938637.63      1611015.49      6939487.07
      1611110.45      6938990.05      1611757.74      6938993.34
      1612174.99      6939538.07        1612505.        6939088.

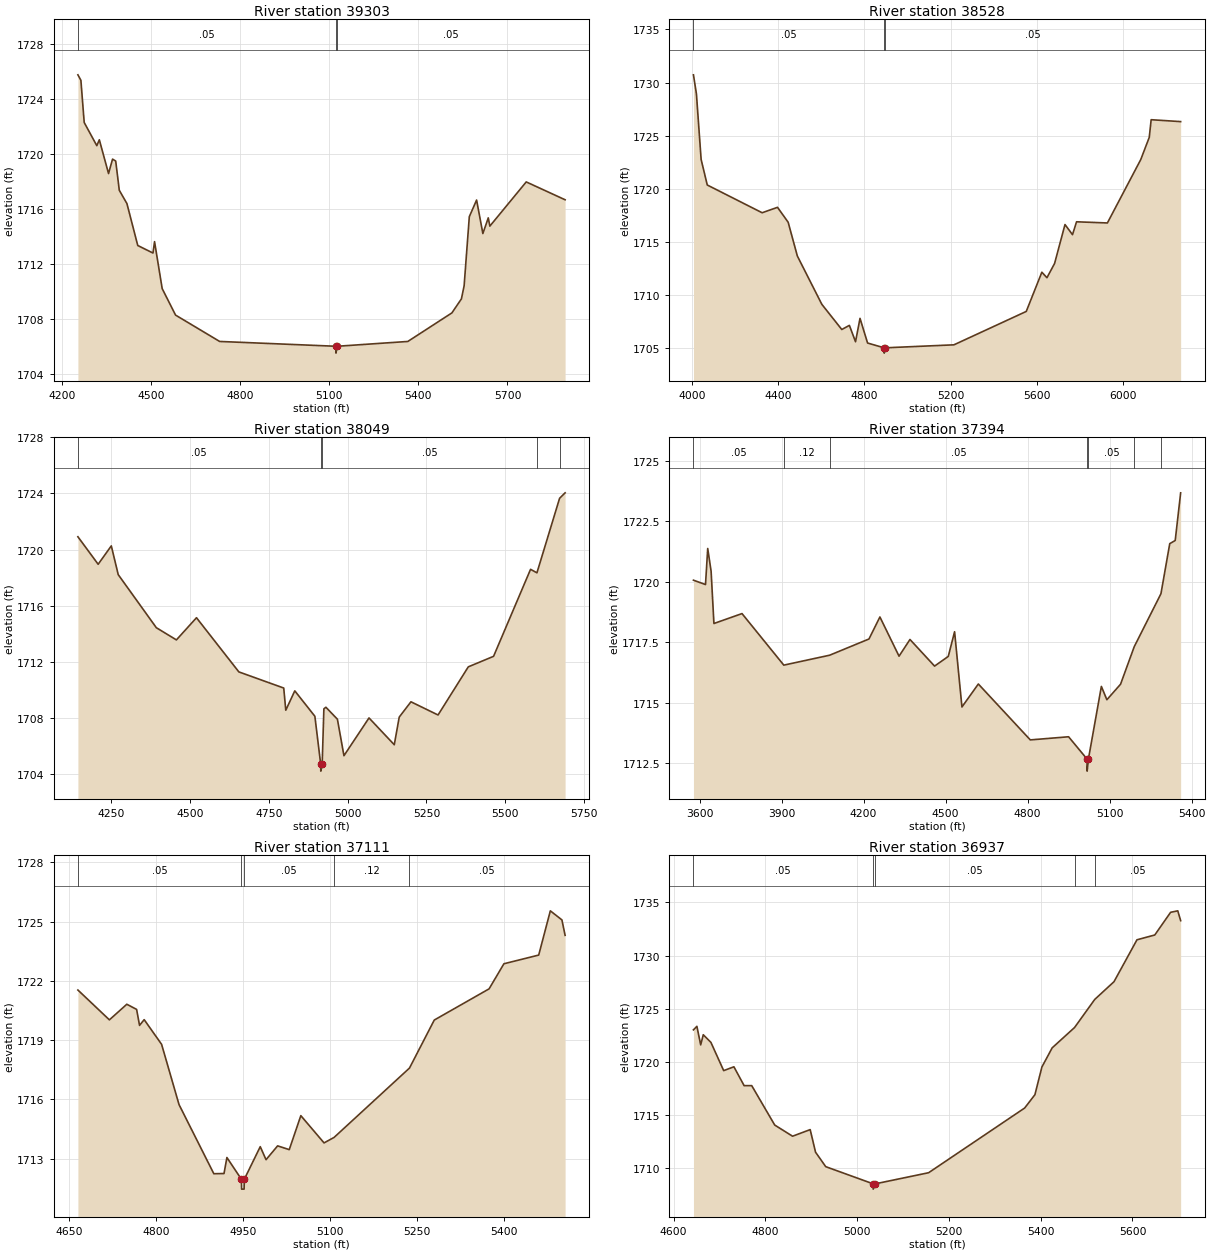
Type RM Length L Ch R = 1 ,39303   ,775,775,775
BEGIN DESCRIPTION:
Deadman 02 66.0
END DESCRIPTION:
XS GIS Cut Line= 3
      1588555.01      6944937.96      1588802.31      6944234.78
      1589079.33      6943384.89
#Sta/Elev= 30
  4254.6 1725.79  4264.7 1725.39  4275.8 1722.32  4318.2 1720.63  4326.7 1721.06
  4357.7  1718.6  4371.2 1719.65  4381.8 1719.51  4393.9 1717.38  4419.6 1716.41
    4456 1713.36  4507.2 1712.81  4512.5 1713.64  4538.2 1710.22  4583.2 1708.29
  4731.6 1706.37  5122.6 1706.02  5122.9 1705.52  5127.2 1706.02  5364.7 1706.37
    5513 1708.45    5545 1709.47  5554.1 1710.42  5571.6 1715.46  5596.1 1716.67
  5617.2 1714.23  5635.4 1715.37  5640.7 1714.77  5763.1 1717.99  5893.9 1716.69
#Mann= 3 ,-1 , 0
  4254.6     .05       0  5122.6    .035       0  5127.2     .05       0
Bank Sta=5122.6,5127.2
XS Rating Curve= 0 ,0
Exp/Cntr=0.3,0.1

Type RM Length L Ch R = 1 ,38528   ,479,479,479
BEGIN DESCRIPTION:
Deadman 02 65.0
END DESCRIPTION:
XS GIS Cut Line= 3
      1588654.99      6945338.01        1589405.        6944688.
      1590580.03      6944212.99
#Sta/Elev= 30
  4007.4 1730.73  4021.2 1728.94    4043 1722.77  4071.5 1720.37    4326 1717.76
  4397.3 1718.27  4446.7 1716.87  4489.4 1713.69  4602.9 1709.15  4695.5 1706.78
  4730.7 1707.17  4759.2 1705.63    4780 1707.83  4815.1 1705.51  4891.7 1705.06
  4892.1 1704.56  4896.3 1705.06  5215.6 1705.34  5551.1 1708.48  5623.5 1712.17
  5647.1 1711.65  5682.5 1712.99  5730.8 1716.65  5765.7  1715.7  5784.4 1716.91
  5927.5  1716.8  6082.2 1722.76  6121.7 1724.85  6130.5 1726.51  6267.3 1726.33
#Mann= 3 ,-1 , 0
  4007.4     .05       0  4891.7     .05       0  4896.3     .05       0
Bank Sta=4891.7,4896.3
XS Rating Curve= 0 ,0
Exp/Cntr=0.3,0.1

Type RM Length L Ch R = 1 ,38049   ,655,655,655
BEGIN DESCRIPTION:
Deadman 02 64.0
END DESCRIPTION:
XS GIS Cut Line= 3
      1588955.02      6945637.98        1589605.        6945088.
      1590205.04      6944737.98
#Sta/Elev= 30
  4143.9 1720.91  4208.2 1718.95  4249.9 1720.26  4271.9 1718.21  4392.8 1714.43
  4456.5 1713.56  4520.2 1715.14  4654.7 1711.28  4797.1 1710.13  4803.6 1708.55
  4832.2 1709.93  4895.9 1708.12  4914.4 1704.71  4914.7 1704.21  4919.1 1704.71
  4924.5 1708.65    4931 1708.76  4967.4 1707.91  4988.2 1705.31  5067.7    1708
  5147.9 1706.09  5163.6 1708.06  5200.8 1709.15  5286.8 1708.21  5382.8 1711.64
    5463 1712.39  5580.4 1718.59  5600.6 1718.34  5672.5 1723.65    5690 1724.04
#Mann= 5 ,-1 , 0
  4143.9     .05       0  4914.4     .05       0  4919.1     .05       0
  5600.6     .12       0  5672.5     .05       0
Bank Sta=4914.4,4919.1
XS Rating Curve= 0 ,0
Exp/Cntr=0.3,0.1

Type RM Length L Ch R = 1 ,37394   ,283,283,283
BEGIN DESCRIPTION:
Mapping XS c256b9d4
END DESCRIPTION:
XS GIS Cut Line= 3
      1590292.62      6946550.92      1590214.38      6946217.38
      1590251.19      6944778.14
#Sta/Elev= 30
  3577.6 1720.07  3621.7 1719.89  3629.8 1721.38  3642.2 1720.44  3652.5 1718.28
  3755.2 1718.69  3908.1 1716.56  4075.9 1716.97  4219.7 1717.64  4259.7 1718.55
  4329.7 1716.93  4369.7 1717.62  4459.7 1716.52  4509.8 1716.92  4532.9 1717.94
  4559.8 1714.83  4619.8 1715.78  4809.9 1713.47  4949.9  1713.6  5017.4 1712.68
  5017.8 1712.18  5022.5 1712.68  5069.9 1715.68    5090 1715.13    5140 1715.77
    5190 1717.32  5287.8 1719.51    5320 1721.58    5340 1721.71  5359.9 1723.68
#Mann= 7 ,-1 , 0
  3577.6     .05       0  3908.1     .12       0  4075.9     .05       0
  5017.4     .05       0  5022.5     .05       0    5190     .12       0
  5287.8     .05       0
Bank Sta=5017.4,5022.5
XS Rating Curve= 0 ,0
Exp/Cntr=0.3,0.1

Type RM Length L Ch R = 1 ,37111   ,174,174,174
BEGIN DESCRIPTION:
Mapping XS b4bec68e
END DESCRIPTION:
XS GIS Cut Line= 2
      1590503.18      6945472.29       1590558.7      6944632.52
#Sta/Elev= 30
  4664.6 1721.54    4719 1720.03  4749.1 1720.82    4766 1720.56  4771.1 1719.75
  4779.1 1720.04  4809.2 1718.79  4839.3 1715.74  4899.4 1712.24    4917 1712.25
    4922 1713.06    4947 1711.96  4947.4 1711.46  4951.7 1711.46  4952.1 1711.96
  4979.6 1713.61  4989.6 1712.95  5009.6 1713.65  5029.7 1713.46  5049.7 1715.18
  5089.8  1713.8  5107.2 1714.08  5237.4 1717.59  5280.2 1720.02  5374.9  1721.6
  5400.5 1722.87  5460.6 1723.31  5480.7 1725.55  5500.7 1725.09  5506.2 1724.31
#Mann= 5 ,-1 , 0
  4664.6     .05       0    4947     .05       0  4952.1     .05       0
  5107.2     .12       0  5237.4     .05       0
Bank Sta=4947,4952.1
XS Rating Curve= 0 ,0
Exp/Cntr=0.3,0.1

Type RM Length L Ch R = 1 ,36937   ,299,299,299
BEGIN DESCRIPTION:
Mapping XS 248ccfc3
END DESCRIPTION:
XS GIS Cut Line= 2
       1590511.6      6945524.69      1590993.38      6944578.49
#Sta/Elev= 30
  4643.2 1723.02  4650.7 1723.35    4659 1721.61  4664.6 1722.56  4681.3 1721.84
  4709.1 1719.19  4731.4 1719.55  4753.6 1717.78  4770.2 1717.78  4820.3 1714.08
  4859.2 1713.03  4897.6 1713.65  4909.3 1711.53  4931.5 1710.17  5034.6 1708.56
    5035 1708.06  5039.7 1708.56  5155.7  1709.6  5365.1 1715.68  5387.4 1716.93
  5402.6 1719.53    5425 1721.33  5473.8 1723.24  5517.8 1725.88  5559.7 1727.54
  5609.8 1731.48  5648.6 1731.93  5683.1 1734.06  5698.7  1734.2    5705 1733.28
#Mann= 5 ,-1 , 0
  4643.2     .05       0  5034.6     .05       0  5039.7     .05       0
  5473.8     .12       0  5517.8     .05       0
Bank Sta=5034.6,5039.7
XS Rating Curve= 0 ,0
Exp/Cntr=0.3,0.1

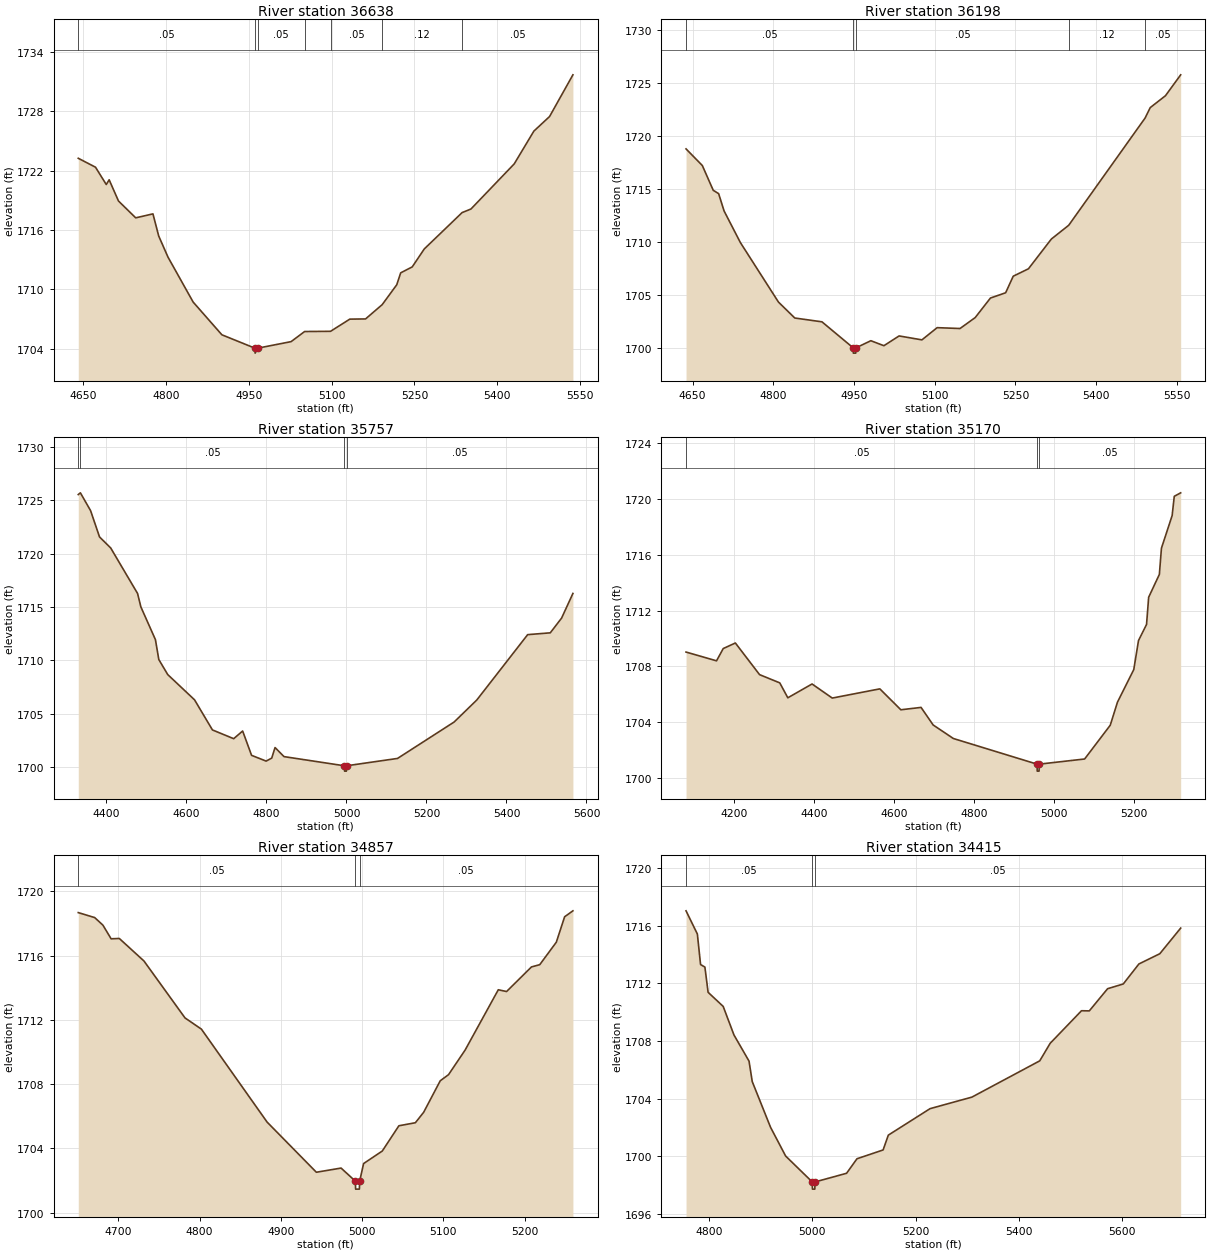
Type RM Length L Ch R = 1 ,36638   ,440,440,440
BEGIN DESCRIPTION:
Deadman 02 61.0
END DESCRIPTION:
XS GIS Cut Line= 3
      1590505.04      6945537.99        1590855.        6945438.
      1591255.02      6945087.98
#Sta/Elev= 30
  4641.5 1723.24  4672.7 1722.34  4692.2 1720.59  4697.4 1721.07  4714.3 1718.93
  4745.5 1717.23  4776.7 1717.63  4787.1  1715.4    4804 1713.26  4849.5 1708.73
  4901.5 1705.43  4961.3 1704.08  4961.7 1703.58  4966.4 1704.08  5026.8 1704.74
  5051.3 1705.76  5098.2 1705.78  5133.1 1707.01  5161.6 1707.03  5191.7 1708.47
  5218.1 1710.48  5225.2 1711.68  5246.1 1712.28  5267.9 1714.09  5336.4 1717.76
  5352.4 1718.12  5430.7 1722.67  5466.3 1725.98  5494.7 1727.45    5537 1731.66
#Mann= 7 ,-1 , 0
  4641.5     .05       0  4961.3     .05       0  4966.4     .05       0
  5051.3     .12       0  5098.2     .05       0  5191.7     .12       0
  5336.4     .05       0
Bank Sta=4961.3,4966.4
XS Rating Curve= 0 ,0
Exp/Cntr=0.3,0.1

Type RM Length L Ch R = 1 ,36198   ,441,441,441
BEGIN DESCRIPTION:
Deadman 02 60.0
END DESCRIPTION:
XS GIS Cut Line= 3
      1590654.97        6945788.        1591005.        6945838.
      1591405.02      6945437.98
#Sta/Elev= 30
  4637.7 1718.81    4668 1717.24  4688.2 1714.91  4698.3 1714.59  4708.4 1712.96
  4738.7 1709.98  4809.5 1704.37  4839.8 1702.87  4890.3 1702.51  4948.3 1700.06
  4948.7 1699.56  4953.1 1699.56  4953.5 1700.06  4981.2 1700.73  5005.4 1700.26
  5033.7 1701.18  5076.1 1700.81  5104.4 1701.96  5146.9 1701.88  5175.1 1702.91
  5203.4 1704.75  5231.7 1705.25  5245.8 1706.81  5274.1 1707.51  5316.6 1710.31
  5348.9 1711.61  5490.9 1721.72  5500.4  1722.7  5528.7 1723.82    5557 1725.79
#Mann= 5 ,-1 , 0
  4637.7     .05       0  4948.3     .03       0  4953.5     .05       0
  5348.9     .12       0  5490.9     .05       0
Bank Sta=4948.3,4953.5
XS Rating Curve= 0 ,0
Exp/Cntr=0.3,0.1

Type RM Length L Ch R = 1 ,35757   ,587,587,587
BEGIN DESCRIPTION:
Deadman 02 59.0
END DESCRIPTION:
XS GIS Cut Line= 3
      1590704.99        6946438.        1591305.        6946138.
      1591704.99      6945738.01
#Sta/Elev= 30
  4329.6 1725.55  4334.9 1725.71  4360.4 1724.04  4382.7 1721.58  4410.7 1720.54
  4477.8 1716.28  4486.1 1715.02  4522.5 1711.95  4530.9 1710.09  4553.2 1708.68
  4620.3 1706.31    4665 1703.49  4718.1 1702.67  4740.5 1703.39  4762.8 1701.11
  4799.2 1700.57  4813.2 1700.85  4821.5 1701.84  4843.9 1700.99    4995 1700.13
  4995.4 1699.63  4999.8 1699.63  5000.2 1700.13  5127.7 1700.82  5269.1 1704.23
  5325.7 1706.29    5453 1712.42  5509.5 1712.59  5537.8 1713.97  5566.1 1716.28
#Mann= 4 ,-1 , 0
  4329.6     .12       0  4334.9     .05       0    4995     .05       0
  5000.2     .05       0
Bank Sta=4995,5000.2
XS Rating Curve= 0 ,0
Exp/Cntr=0.3,0.1

Type RM Length L Ch R = 1 ,35170   ,313,313,313
BEGIN DESCRIPTION:
Deadman 02 58.0
END DESCRIPTION:
XS GIS Cut Line= 3
      1591969.04      6947150.16      1591857.51      6946238.15
        1591955.      6945937.99
#Sta/Elev= 30
  4081.2 1709.03  4157.3  1708.4    4174 1709.28  4204.3 1709.68  4264.7 1707.41
  4315.1 1706.82  4335.2 1705.75  4395.7 1706.74  4446.1 1705.73  4564.8 1706.39
  4617.3 1704.89  4667.7 1705.06  4697.9  1703.8  4748.3 1702.83  4957.2 1700.99
  4957.6 1700.49  4962.2 1700.49  4962.6 1700.99  5075.9 1701.36  5139.8 1703.78
  5157.9 1705.44  5198.5 1707.77  5210.4 1709.86  5230.4 1711.01  5235.7 1712.96
  5262.4  1714.6  5267.6 1716.48  5294.3 1718.82  5299.6  1720.2  5315.6 1720.45
#Mann= 3 ,-1 , 0
  4081.2     .05       0  4957.2     .03       0  4962.6     .05       0
Bank Sta=4957.2,4962.6
XS Rating Curve= 0 ,0
Exp/Cntr=0.3,0.1

Type RM Length L Ch R = 1 ,34857   ,442,442,442
BEGIN DESCRIPTION:
Deadman 02 57.0
END DESCRIPTION:
XS GIS Cut Line= 3
        1592205.        6946538.        1592155.        6946188.
        1592105.      6945938.01
#Sta/Elev= 30
  4650.8 1718.67    4671 1718.36  4681.1 1717.89  4691.2 1717.04  4701.3 1717.06
  4731.6 1715.66  4782.1 1712.12  4802.3 1711.42  4883.1 1705.64  4943.7 1702.52
  4974.1 1702.78  4991.6 1701.97    4992 1701.47  4996.6 1701.47    4997 1701.97
  5001.8 1703.06  5024.8 1703.84  5045.2 1705.41  5065.5  1705.6  5075.7 1706.25
  5096.1 1708.21  5106.3 1708.59  5126.7 1710.12  5167.5 1713.87  5177.7 1713.76
  5208.3 1715.29  5218.5 1715.43  5238.9 1716.83  5249.1 1718.41  5259.3 1718.78
#Mann= 3 ,-1 , 0
  4650.8     .05       0  4991.6     .03       0    4997     .05       0
Bank Sta=4991.6,4997
XS Rating Curve= 0 ,0
Exp/Cntr=0.3,0.1

Type RM Length L Ch R = 1 ,34415   ,338,338,338
BEGIN DESCRIPTION:
Deadman 02 56.0
END DESCRIPTION:
XS GIS Cut Line= 3
      1592354.99      6946488.01        1592555.        6946338.
        1592455.      6945638.02
#Sta/Elev= 30
  4755.9 1717.04  4777.8 1715.43    4784 1713.31  4792.4 1713.13  4798.6 1711.38
  4827.8  1710.4  4848.6 1708.42  4877.8  1706.6    4884 1705.18  4919.5    1702
  4948.6 1700.01  5000.1 1698.21  5000.5 1697.71  5005.1 1697.71  5005.5 1698.21
  5066.5 1698.81  5086.7 1699.82  5137.2 1700.43  5147.3 1701.46  5228.1  1703.3
    5309  1704.1  5440.3 1706.62  5460.5 1707.84  5521.1  1710.1  5536.2 1710.09
  5571.6 1711.63  5601.9 1711.96  5632.2 1713.35  5672.6 1714.06    5713 1715.84
#Mann= 3 ,-1 , 0
  4755.9     .05       0  5000.1     .05       0  5005.5     .05       0
Bank Sta=5000.1,5005.5
XS Rating Curve= 0 ,0
Exp/Cntr=0.3,0.1

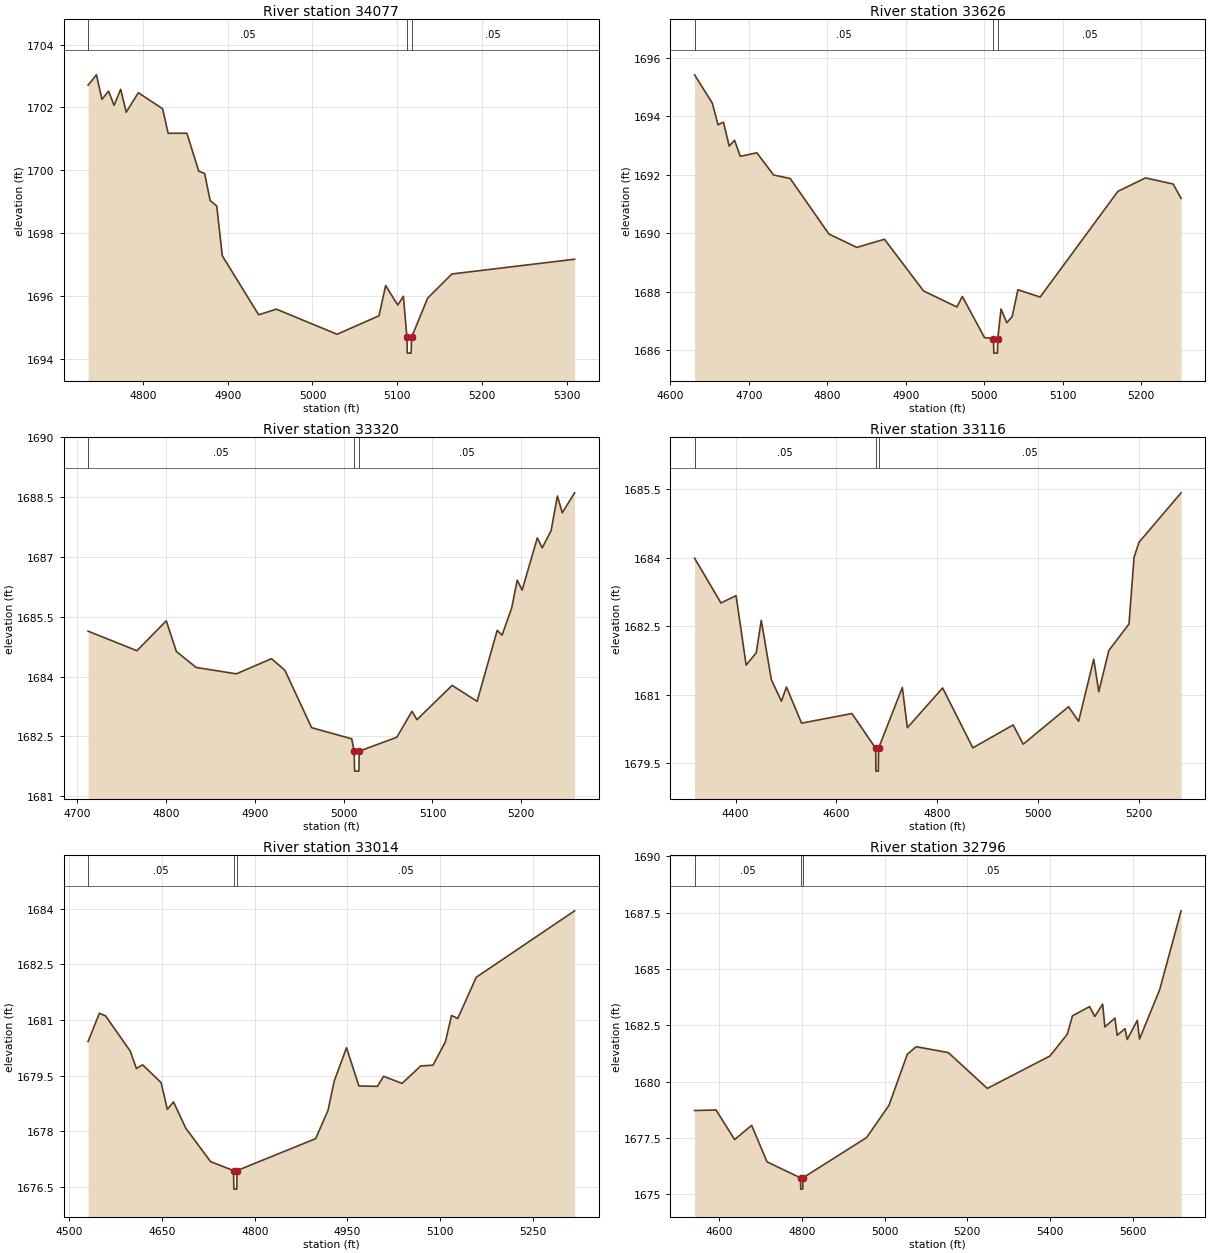
Type RM Length L Ch R = 1 ,34077   ,451,451,451
BEGIN DESCRIPTION:
Mapping XS 37f24bbb
END DESCRIPTION:
XS GIS Cut Line= 2
      1592641.59      6946747.93      1593009.94      6946308.62
#Sta/Elev= 30
  4735.6 1702.71  4745.4 1703.04  4751.9 1702.26  4759.7 1702.52  4766.2 1702.07
    4774 1702.58  4780.5 1701.85  4794.8 1702.47  4823.4 1701.96  4829.9 1701.18
    4852 1701.18    4866 1699.97  4872.9  1699.9  4879.4 1699.04  4887.2 1698.86
  4893.7 1697.28  4936.6  1695.4  4957.5 1695.58    5029 1694.78  5078.4 1695.37
  5086.2 1696.33  5100.5 1695.71  5107.1 1695.99  5111.3 1694.68  5111.7 1694.18
  5116.3 1694.18  5116.7 1694.68  5135.7 1695.93  5164.3  1696.7  5308.9 1697.17
#Mann= 3 ,-1 , 0
  4735.6     .05       0  5111.3     .05       0  5116.7     .05       0
Bank Sta=5111.3,5116.7
XS Rating Curve= 0 ,0
Exp/Cntr=0.3,0.1

Type RM Length L Ch R = 1 ,33626   ,306,306,306
BEGIN DESCRIPTION:
Mapping XS c697f127
END DESCRIPTION:
XS GIS Cut Line= 2
      1592861.23      6947116.35      1593312.77      6946691.77
#Sta/Elev= 30
  4630.9 1695.42  4653.5 1694.45  4660.8 1693.71  4667.7  1693.8    4675 1692.98
  4681.8 1693.18  4689.1 1692.63  4710.2 1692.75  4731.6 1691.99  4752.7 1691.87
    4802 1689.97  4837.6 1689.51  4872.8 1689.79  4922.6 1688.02  4965.1 1687.47
    4972 1687.83  5000.3 1686.42  5011.7 1686.39  5012.1 1685.89  5016.7 1685.89
  5017.2 1686.39  5021.3  1687.4  5028.6 1686.93  5035.5 1687.14  5042.8 1688.06
  5071.1 1687.81  5170.2 1691.43  5205.4 1691.89  5240.6 1691.68  5250.7 1691.19
#Mann= 3 ,-1 , 0
  4630.9     .05       0  5011.7     .05       0  5017.2     .05       0
Bank Sta=5011.7,5017.2
XS Rating Curve= 0 ,0
Exp/Cntr=0.3,0.1

Type RM Length L Ch R = 1 ,33320   ,204,204,204
BEGIN DESCRIPTION:
Mapping XS 921a0297
END DESCRIPTION:
XS GIS Cut Line= 2
      1593239.43       6947307.5       1593477.8      6946814.18
#Sta/Elev= 30
  4712.2 1685.14  4767.2 1684.65  4800.2  1685.4  4811.6 1684.63  4833.9 1684.23
  4879.1 1684.07  4918.7 1684.45  4933.8 1684.16  4963.9 1682.72  5009.1 1682.44
  5011.8 1682.13  5012.3 1681.63  5017.1 1681.63  5017.5 1682.13  5059.9 1682.48
  5076.9 1683.13  5082.5 1682.92  5122.1 1683.78  5150.3 1683.38  5172.9 1685.16
  5178.4 1685.04  5189.2 1685.72  5195.5 1686.42    5201 1686.17  5218.1 1687.48
  5223.6 1687.23  5233.6 1687.66  5240.7 1688.53  5246.2 1688.11  5260.1 1688.61
#Mann= 3 ,-1 , 0
  4712.2     .05       0  5011.8     .05       0  5017.5     .05       0
Bank Sta=5011.8,5017.5
XS Rating Curve= 0 ,0
Exp/Cntr=0.3,0.1

Type RM Length L Ch R = 1 ,33116   ,102,102,102
BEGIN DESCRIPTION:
Mapping XS f9b8d986
END DESCRIPTION:
XS GIS Cut Line= 2
      1593547.56      6947770.36      1593558.41      6946804.62
#Sta/Elev= 30
  4318.6 1683.99    4371 1683.01    4401 1683.17    4421 1681.65    4441 1681.92
    4451 1682.63    4471 1681.33    4491 1680.86    4501 1681.17    4531 1680.38
    4631 1680.59  4678.1 1679.83  4678.6 1679.33  4683.4 1679.33  4683.8 1679.83
    4731 1681.16    4741 1680.28    4811 1681.15    4871 1679.84    4951 1680.34
    4971 1679.92    5061 1680.74    5081 1680.42    5111 1681.78    5121 1681.07
    5141 1681.97    5181 1682.55    5191 1684.01    5201 1684.34  5284.4 1685.42
#Mann= 3 ,-1 , 0
  4318.6     .05       0  4678.1     .05       0  4683.8     .05       0
Bank Sta=4678.1,4683.8
XS Rating Curve= 0 ,0
Exp/Cntr=0.3,0.1

Type RM Length L Ch R = 1 ,33014   ,218,218,218
BEGIN DESCRIPTION:
Mapping XS 7071ff60
END DESCRIPTION:
XS GIS Cut Line= 2
      1593638.57      6947596.24      1593648.71       6946808.8
#Sta/Elev= 30
  4530.2 1680.42  4548.4 1681.18  4558.4 1681.11  4598.4 1680.16  4608.4 1679.69
  4618.4 1679.79  4648.4 1679.31  4658.4 1678.59  4668.4 1678.79  4688.4 1678.08
  4728.5 1677.18  4765.6 1676.94  4766.1 1676.44  4770.9 1676.44  4771.3 1676.94
  4898.5  1677.8  4918.5 1678.56  4928.5 1679.35  4948.5 1680.25  4968.5 1679.22
  4998.5 1679.21  5008.5 1679.48  5038.5 1679.29  5068.5 1679.76  5088.5 1679.78
  5108.5 1680.41  5118.5 1681.12  5128.5 1681.04  5158.5 1682.15  5317.7 1683.94
#Mann= 3 ,-1 , 0
  4530.2     .05       0  4765.6     .03       0  4771.3     .05       0
Bank Sta=4765.6,4771.3
XS Rating Curve= 0 ,0
Exp/Cntr=0.3,0.1

Type RM Length L Ch R = 1 ,32796   ,371,371,371
BEGIN DESCRIPTION:
Mapping XS 163a2bea
END DESCRIPTION:
XS GIS Cut Line= 2
      1593675.76      6947606.34        1594108.      6946512.23
#Sta/Elev= 30
  4540.7 1678.72  4592.7 1678.74  4637.5 1677.43  4678.7 1678.06  4715.9 1676.44
  4796.9 1675.73  4797.4 1675.23  4802.2 1675.23  4802.6 1675.73  4956.7 1677.52
  5010.8 1678.95    5055 1681.21  5076.5 1681.55  5154.1 1681.29  5248.6  1679.7
  5400.2 1681.14  5442.1 1682.11  5454.3 1682.92  5495.9 1683.33  5508.4 1682.89
  5527.4 1683.44  5532.8 1682.43  5557.1 1682.82  5562.5 1682.06  5581.5 1682.35
  5586.9 1681.87  5611.2 1682.72  5616.6 1681.89  5665.3 1684.08  5717.1 1687.58
#Mann= 3 ,-1 , 0
  4540.7     .05       0  4796.9     .03       0  4802.6     .05       0
Bank Sta=4796.9,4802.6
XS Rating Curve= 0 ,0
Exp/Cntr=0.3,0.1

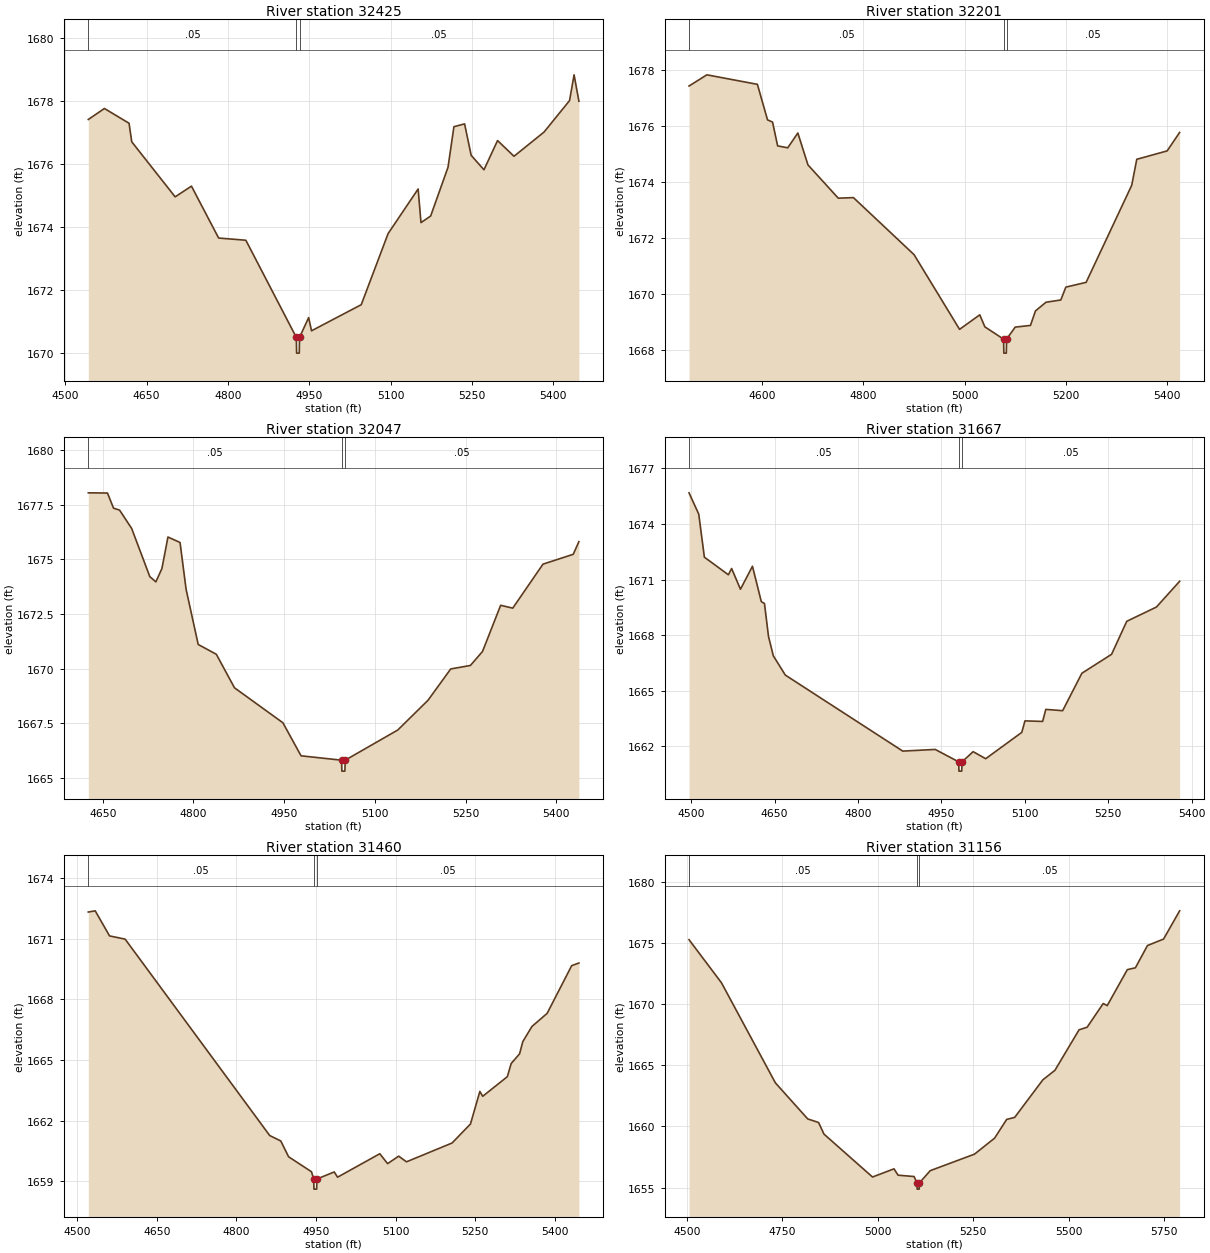
Type RM Length L Ch R = 1 ,32425   ,224,224,224
BEGIN DESCRIPTION:
Mapping XS 794da437
END DESCRIPTION:
XS GIS Cut Line= 3
      1593735.35      6947588.71      1594060.69        6947564.
      1594261.99      6947021.73
#Sta/Elev= 30
  4542.7 1677.42  4572.4 1677.77  4617.8  1677.3  4622.8 1676.71  4702.8 1674.96
  4732.9  1675.3    4783 1673.65  4833.2 1673.58  4926.3 1670.49  4926.8 1669.99
  4931.7 1669.99  4932.2 1670.49    4949 1671.12  4954.3  1670.7    5046 1671.53
  5095.5 1673.79  5150.9 1675.21  5156.2 1674.14    5174 1674.35    5206  1675.9
  5216.9 1677.19  5236.6 1677.28  5248.7 1676.28  5272.3 1675.82  5297.4 1676.75
  5327.7 1676.25  5383.1 1677.02  5430.1 1678.02  5438.5 1678.84  5447.4    1678
#Mann= 3 ,-1 , 0
  4542.7     .05       0  4926.3     .03       0  4932.2     .05       0
Bank Sta=4926.3,4932.2
XS Rating Curve= 0 ,0
Exp/Cntr=0.3,0.1

Type RM Length L Ch R = 1 ,32201   ,154,154,154
BEGIN DESCRIPTION:
Mapping XS 5a0224aa
END DESCRIPTION:
XS GIS Cut Line= 3
      1593719.71      6947602.99      1594317.87      6947599.62
      1594689.65      6947575.96
#Sta/Elev= 30
  4454.8 1677.44  4490.1 1677.84  4590.1  1677.5  4610.1 1676.23  4620.1 1676.15
  4630.1  1675.3  4650.1 1675.23  4670.1 1675.76  4690.1 1674.62  4750.1 1673.43
  4780.1 1673.45  4900.1 1671.41  4990.1 1668.74  5030.1 1669.26  5040.1 1668.83
  5077.2 1668.39  5077.7 1667.89  5082.6 1667.89  5083.1 1668.39  5100.2 1668.82
  5130.3 1668.88  5140.3  1669.4  5161.2 1669.71  5190.4 1669.79  5200.4 1670.25
  5240.5 1670.42  5330.7 1673.89  5340.7 1674.82  5400.8 1675.12  5425.5 1675.78
#Mann= 3 ,-1 , 0
  4454.8     .05       0  5077.2     .03       0  5083.1     .05       0
Bank Sta=5077.2,5083.1
XS Rating Curve= 0 ,0
Exp/Cntr=0.3,0.1

Type RM Length L Ch R = 1 ,32047   ,380,380,380
BEGIN DESCRIPTION:
Mapping XS 2b569f5b
END DESCRIPTION:
XS GIS Cut Line= 2
      1593983.34      6947728.04      1594794.38      6947707.76
#Sta/Elev= 30
  4626.1 1678.04  4657.8 1678.03  4667.8 1677.34  4677.8 1677.25  4697.8 1676.41
  4727.8 1674.21  4737.8 1673.97  4747.8 1674.58  4757.8 1676.02  4777.8 1675.77
  4787.8 1673.63  4807.8 1671.11  4837.8 1670.66  4867.8 1669.13  4947.9 1667.53
  4977.9 1666.02  5044.9 1665.82  5045.4 1665.32  5050.4 1665.32  5050.9 1665.82
  5137.9  1667.2  5187.9 1668.56  5225.4 1669.99    5258 1670.15    5278 1670.79
    5308  1672.9    5328 1672.77    5378 1674.78    5428 1675.23  5437.4 1675.81
#Mann= 3 ,-1 , 0
  4626.1     .05       0  5044.9     .03       0  5050.9     .05       0
Bank Sta=5044.9,5050.9
XS Rating Curve= 0 ,0
Exp/Cntr=0.3,0.1

Type RM Length L Ch R = 1 ,31667   ,207,207,207
BEGIN DESCRIPTION:
Mapping XS db4b9baa
END DESCRIPTION:
XS GIS Cut Line= 2
      1594040.76      6948309.33      1594807.93      6947873.36
#Sta/Elev= 30
    4496 1675.68  4513.5 1674.53  4523.6 1672.21  4566.8 1671.26  4572.6  1671.6
  4588.5 1670.48  4610.1 1671.72    4626 1669.81  4631.7 1669.71  4638.9 1667.94
  4647.6 1666.89  4669.2 1665.85  4880.4 1661.75  4938.8 1661.84    4981 1661.17
  4981.5 1660.67  4986.5 1660.67    4987 1661.17    5007 1661.72  5029.6 1661.34
  5094.5 1662.76  5100.2 1663.38    5132 1663.35  5137.7    1664    5168 1663.93
  5202.6 1665.95    5256 1666.97  5283.3 1668.75  5336.7 1669.52  5378.4 1670.91
#Mann= 3 ,-1 , 0
    4496     .05       0    4981     .05       0    4987     .05       0
Bank Sta=4981,4987
XS Rating Curve= 0 ,0
Exp/Cntr=0.3,0.1

Type RM Length L Ch R = 1 ,31460   ,304,304,304
BEGIN DESCRIPTION:
Mapping XS 95a7ff44
END DESCRIPTION:
XS GIS Cut Line= 3
      1594163.61      6948523.55      1594736.06      6948111.71
      1594825.97      6947911.47
#Sta/Elev= 30
  4520.9 1672.32  4533.9 1672.38  4560.9 1671.14  4590.3 1670.98  4862.8 1661.27
  4883.7    1661  4898.4 1660.22  4941.5 1659.48  4945.7 1659.12  4946.2 1658.62
  4951.3 1658.62  4951.8 1659.12  4984.4 1659.47  4990.7 1659.21  5070.3 1660.37
    5085 1659.88  5105.9 1660.25  5120.6 1659.97  5206.5  1660.9  5241.2 1661.84
  5258.9 1663.45  5264.3 1663.21  5310.7 1664.18  5317.9 1664.83  5333.8 1665.31
  5339.8 1665.91    5357 1666.66  5385.7 1667.31    5432 1669.67  5445.6  1669.8
#Mann= 3 ,-1 , 0
  4520.9     .05       0  4945.7     .05       0  4951.8     .05       0
Bank Sta=4945.7,4951.8
XS Rating Curve= 0 ,0
Exp/Cntr=0.3,0.1

Type RM Length L Ch R = 1 ,31156   ,341,341,341
BEGIN DESCRIPTION:
Deadman 02 49.0
END DESCRIPTION:
XS GIS Cut Line= 3
        1594355.        6948838.        1594705.        6948488.
      1594954.99      6947738.04
#Sta/Elev= 30
  4505.5 1675.27  4590.4 1671.75  4731.8 1663.56  4816.6 1660.61  4844.9 1660.32
  4859.1 1659.37  4986.3 1655.86  5042.6 1656.53  5053.2 1656.01  5095.3  1655.9
  5102.8 1655.37  5103.3 1654.87  5108.5 1654.87    5109 1655.37  5137.5 1656.38
  5253.5 1657.73  5306.2 1659.04  5337.8 1660.57  5358.9 1660.74  5432.7 1663.81
  5464.3 1664.59  5527.5  1667.9  5548.6 1668.11  5590.8 1670.05  5601.3 1669.88
    5654 1672.82  5675.1 1672.97  5706.7 1674.79  5748.9 1675.32    5791 1677.63
#Mann= 3 ,-1 , 0
  4505.5     .05       0  5102.8     .05       0    5109     .05       0
Bank Sta=5102.8,5109
XS Rating Curve= 0 ,0
Exp/Cntr=0.3,0.1

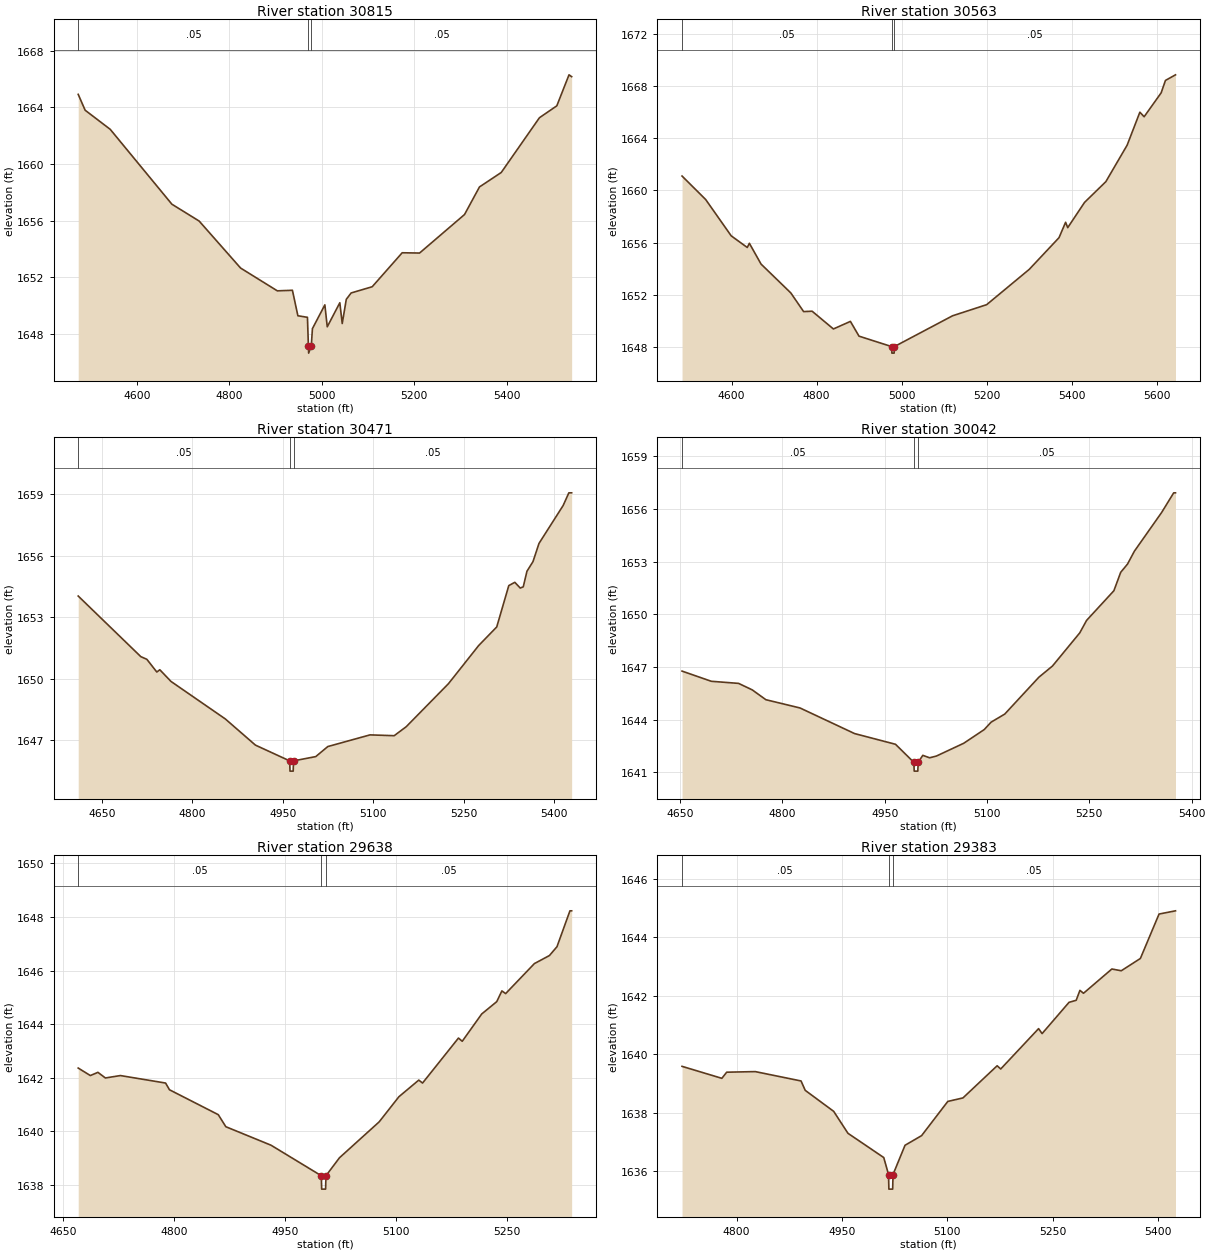
Type RM Length L Ch R = 1 ,30815   ,252,252,252
BEGIN DESCRIPTION:
Mapping XS 7e86afff
END DESCRIPTION:
XS GIS Cut Line= 3
      1594591.63      6948806.14       1595010.7      6948593.22
      1595189.66      6948022.58
#Sta/Elev= 30
  4472.6 1664.92  4487.6  1663.8  4541.9 1662.45  4675.4 1657.16  4734.4 1655.97
  4824.1 1652.65  4903.6 1651.04  4936.3 1651.08  4948.1 1649.28  4968.8 1649.17
  4970.9 1647.14  4971.4 1646.64  4977.1 1647.14  4979.6 1648.37  5006.5 1650.05
  5011.7  1648.5  5038.9  1650.2  5044.1 1648.73  5052.9 1650.44  5063.4 1650.89
    5109 1651.33  5173.9 1653.73  5211.5 1653.71  5308.8 1656.43  5341.2 1658.38
  5388.3  1659.4    5471 1663.27  5508.6 1664.11    5535  1666.3  5540.7 1666.17
#Mann= 3 ,-1 , 0
  4472.6     .05       0  4970.9     .05       0  4977.1     .05       0
Bank Sta=4970.9,4977.1
XS Rating Curve= 0 ,0
Exp/Cntr=0.3,0.1

Type RM Length L Ch R = 1 ,30563   ,92,92,92
BEGIN DESCRIPTION:
Deadman 02 48.0
END DESCRIPTION:
XS GIS Cut Line= 3
      1595243.89      6949103.54      1595264.17      6948586.47
      1595240.51      6947944.37
#Sta/Elev= 30
  4483.7 1661.09  4539.3 1659.29  4599.3 1656.51    4637 1655.62    4642 1655.94
  4669.4 1654.35  4739.4 1652.14  4769.5 1650.71  4789.5 1650.74  4839.5 1649.38
  4879.5 1649.96  4899.7 1648.83  4976.5 1648.03    4977 1647.53  4982.3 1647.53
  4982.8 1648.03  5119.7 1650.39  5199.8 1651.24  5299.8 1653.94  5369.9 1656.37
  5385.4 1657.55  5390.4 1657.14  5429.9 1659.07    5480 1660.66    5530 1663.45
    5560 1665.98    5570 1665.63    5610 1667.46  5620.1 1668.41  5643.7 1668.84
#Mann= 3 ,-1 , 0
  4483.7     .05       0  4976.5     .03       0  4982.8     .05       0
Bank Sta=4976.5,4982.8
XS Rating Curve= 0 ,0
Exp/Cntr=0.3,0.1

Type RM Length L Ch R = 1 ,30471   ,429,429,429
BEGIN DESCRIPTION:
Mapping XS c86db497
END DESCRIPTION:
XS GIS Cut Line= 2
      1595362.18      6948971.75      1595348.66      6948153.86
#Sta/Elev= 30
  4610.8 1654.04  4714.6 1651.08  4724.6 1650.95  4741.1 1650.33  4746.1 1650.44
  4764.6 1649.87  4854.6 1648.04  4904.6 1646.76  4961.4 1645.99  4961.9 1645.49
  4967.2 1645.49  4967.7 1645.99  5004.6  1646.2  5024.6 1646.69  5094.6 1647.26
  5134.6 1647.22  5154.6 1647.66  5224.6 1649.76  5274.6 1651.62  5304.6 1652.53
  5324.6 1654.55  5334.6 1654.71  5343.6 1654.43  5348.6 1654.49  5354.7 1655.25
  5364.7 1655.72  5374.7 1656.61  5414.7 1658.46  5424.2 1659.08  5428.8 1659.08
#Mann= 3 ,-1 , 0
  4610.8     .05       0  4961.4     .03       0  4967.7     .05       0
Bank Sta=4961.4,4967.7
XS Rating Curve= 0 ,0
Exp/Cntr=0.3,0.1

Type RM Length L Ch R = 1 ,30042   ,404,404,404
BEGIN DESCRIPTION:
Mapping XS cf7890d7
END DESCRIPTION:
XS GIS Cut Line= 2
       1595723.8      6948910.88      1595737.32      6948187.71
#Sta/Elev= 30
    4653 1646.76  4695.9 1646.18  4735.9 1646.06  4755.9 1645.69  4775.9 1645.13
  4825.9 1644.66  4905.9  1643.2  4965.9 1642.59  4992.8 1641.56  4993.3 1641.06
  4998.6 1641.06  4999.1 1641.56  5005.9 1641.96  5015.9 1641.82  5025.9 1641.92
    5066 1642.65    5096 1643.43    5106 1643.85    5126 1644.31    5176 1646.41
    5196 1647.05    5236 1648.94    5246 1649.65    5286 1651.34    5296 1652.39
    5306 1652.86    5316 1653.59    5356  1655.8  5373.7 1656.92  5376.3 1656.92
#Mann= 3 ,-1 , 0
    4653     .05       0  4992.8     .05       0  4999.1     .05       0
Bank Sta=4992.8,4999.1
XS Rating Curve= 0 ,0
Exp/Cntr=0.3,0.1

Type RM Length L Ch R = 1 ,29638   ,255,255,255
BEGIN DESCRIPTION:
Mapping XS 4804a419
END DESCRIPTION:
XS GIS Cut Line= 2
      1596038.11      6948904.13      1596156.39      6948248.51
#Sta/Elev= 30
  4670.6 1642.36    4687 1642.08  4697.2  1642.2  4707.3 1641.99  4727.6 1642.08
  4788.6  1641.8  4793.8 1641.55  4859.7 1640.62  4869.9 1640.17  4930.9 1639.48
  4998.8 1638.34  4999.3 1637.84  5004.6 1637.84  5005.1 1638.34  5023.3 1639.01
  5076.9 1640.35  5103.6 1641.29  5130.4 1641.91  5135.5  1641.8    5184 1643.48
  5189.1 1643.36  5215.4 1644.38  5235.7 1644.84  5242.6 1645.24  5247.7 1645.14
  5286.5 1646.26  5306.8 1646.56    5317 1646.89  5334.5 1648.23  5336.8 1648.23
#Mann= 3 ,-1 , 0
  4670.6     .05       0  4998.8     .05       0  5005.1     .05       0
Bank Sta=4998.8,5005.1
XS Rating Curve= 0 ,0
Exp/Cntr=0.3,0.1

Type RM Length L Ch R = 1 ,29383   ,300,300,300
BEGIN DESCRIPTION:
Mapping XS 87066316
END DESCRIPTION:
XS GIS Cut Line= 2
      1596280.35      6948910.65      1596403.89       6948218.8
#Sta/Elev= 30
  4722.2 1639.59  4778.9 1639.18  4785.8 1639.39  4826.5 1639.41  4891.7 1639.09
  4897.6 1638.77  4938.2 1638.05  4958.5  1637.3  5009.5 1636.47  5016.3 1635.89
  5016.8 1635.39  5022.2 1635.39  5022.7 1635.89  5039.8 1636.89  5063.4 1637.22
  5100.7 1638.39  5122.3 1638.51    5171 1639.61  5176.1  1639.5    5230 1640.88
    5235 1640.71  5273.4 1641.78  5283.6 1641.85  5288.9 1642.19    5294 1642.09
  5334.4 1642.92  5347.8 1642.86    5375 1643.28  5401.6  1644.8    5425 1644.91
#Mann= 3 ,-1 , 0
  4722.2     .05       0  5016.3     .05       0  5022.7     .05       0
Bank Sta=5016.3,5022.7
XS Rating Curve= 0 ,0
Exp/Cntr=0.3,0.1