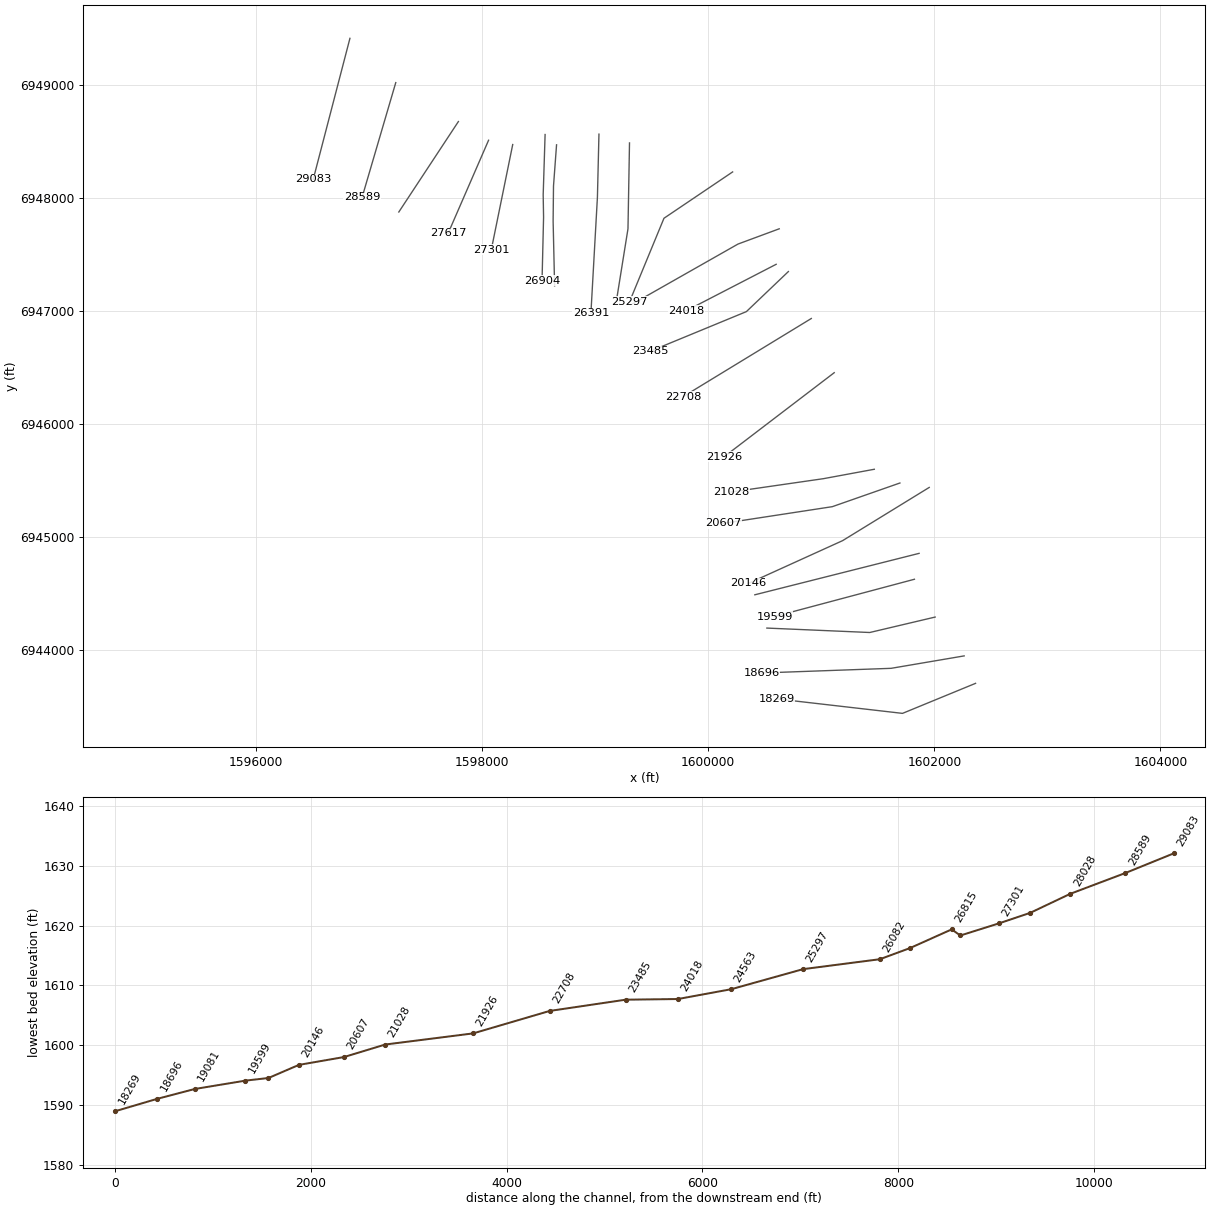
HEC-RAS study Deadman 02.prj: Deadman 02 Base Level Engineering

--- Deadman 02.g01 (geometry) --- (continued)

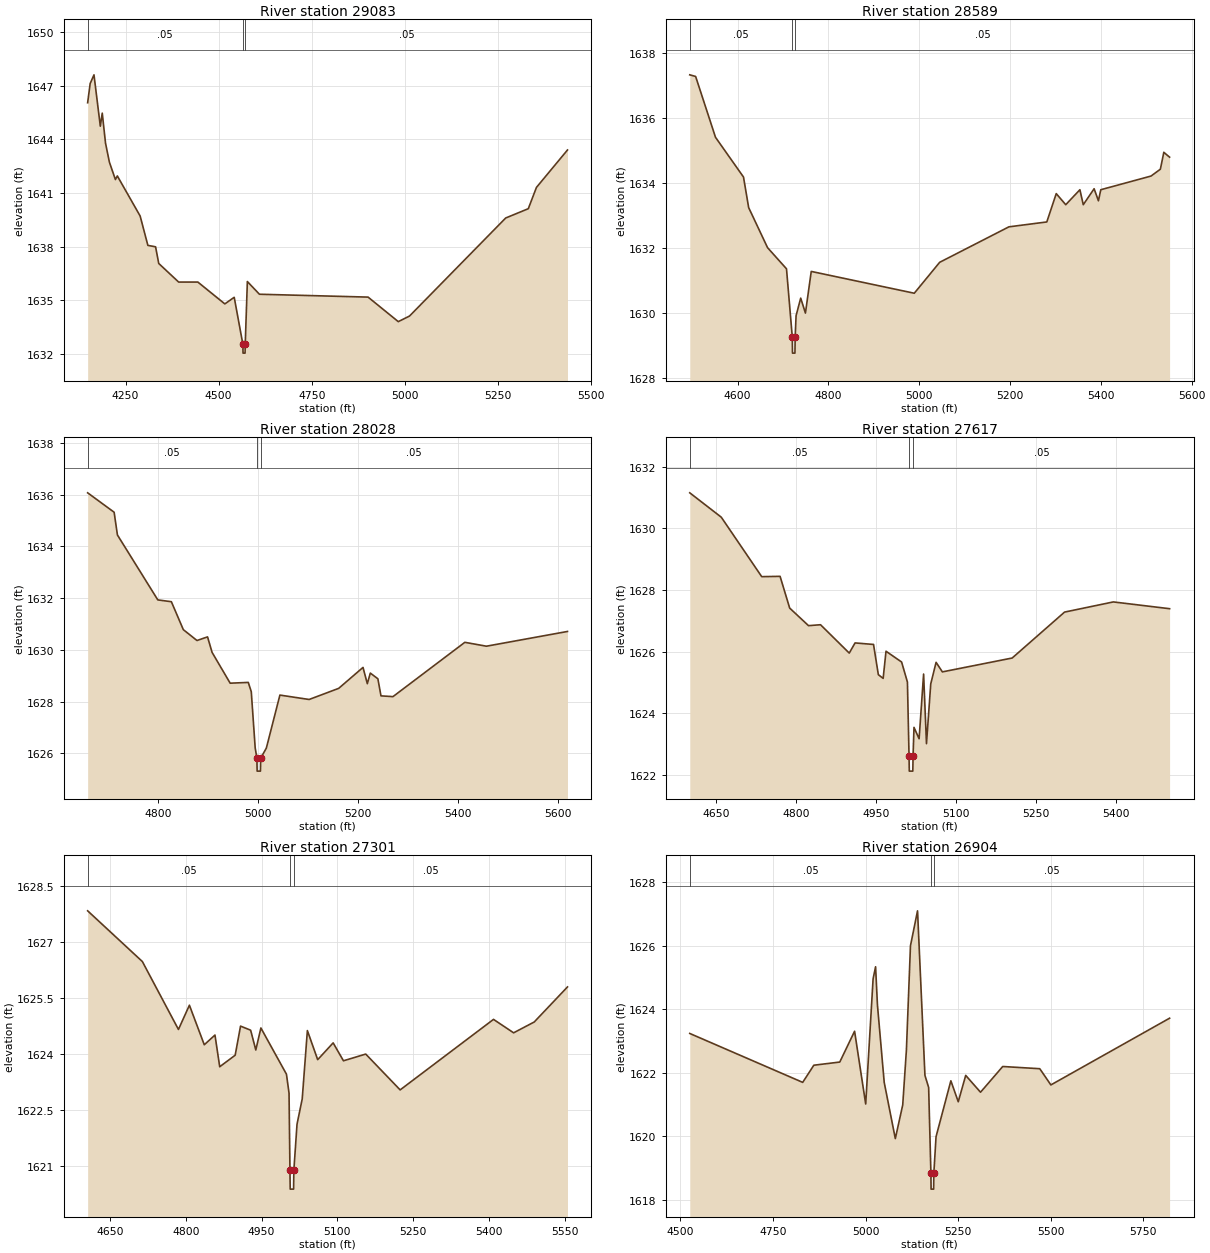
Type RM Length L Ch R = 1 ,29083   ,494,494,494
BEGIN DESCRIPTION:
Mapping XS 1ac94856
END DESCRIPTION:
XS GIS Cut Line= 2
      1596828.94      6949414.49      1596504.49       6948167.4
#Sta/Elev= 30
  4148.3 1646.04    4155 1647.11  4165.3  1647.6  4182.3 1644.73  4187.5 1645.46
  4196.3 1643.78  4206.7 1642.72  4222.8 1641.75    4228 1641.95  4289.3 1639.71
    4310 1638.07  4330.7 1637.99  4339.2 1637.06  4392.7 1636.02  4444.3 1636.02
  4516.7  1634.8  4541.9 1635.17  4565.1 1632.55  4565.6 1632.05    4571 1632.05
  4571.5 1632.55  4577.2 1636.05  4609.6 1635.34  4901.4 1635.18  4982.5 1633.81
  5012.6 1634.12    5271  1639.6  5331.7 1640.12  5353.6 1641.31  5436.9  1643.4
#Mann= 3 ,-1 , 0
  4148.3     .05       0  4565.1     .05       0  4571.5     .05       0
Bank Sta=4565.1,4571.5
XS Rating Curve= 0 ,0
Exp/Cntr=0.3,0.1

Type RM Length L Ch R = 1 ,28589   ,561,561,561
BEGIN DESCRIPTION:
Mapping XS 772ec94d
END DESCRIPTION:
XS GIS Cut Line= 2
      1597234.48      6949022.41      1596937.08      6948008.53
#Sta/Elev= 30
  4494.8 1637.32  4507.7 1637.27  4551.5  1635.4  4613.1 1634.18  4624.5 1633.24
  4666.1 1632.01  4707.8 1631.36  4720.5 1629.27    4721 1628.77  4726.4 1628.77
  4726.9 1629.27  4728.9 1629.92  4739.1 1630.46  4749.5    1630  4762.3 1631.28
  4989.2 1630.61  5045.1 1631.56  5197.6 1632.65    5281  1632.8  5301.8 1633.67
  5322.7 1633.33  5353.9 1633.79  5361.3 1633.33  5385.2 1633.82  5394.7 1633.45
  5399.9 1633.79  5510.5 1634.21  5531.1 1634.42  5538.7 1634.94  5551.4 1634.79
#Mann= 3 ,-1 , 0
  4494.8     .05       0  4720.5    .035       0  4726.9     .05       0
Bank Sta=4720.5,4726.9
XS Rating Curve= 0 ,0
Exp/Cntr=0.3,0.1

Type RM Length L Ch R = 1 ,28028   ,411,411,411
BEGIN DESCRIPTION:
Mapping XS 800fc63b
END DESCRIPTION:
XS GIS Cut Line= 2
      1597788.72      6948677.68      1597261.51      6947876.72
#Sta/Elev= 30
  4659.3 1636.07  4712.2 1635.32  4718.8 1634.44  4799.5 1631.93  4826.6 1631.86
  4850.5 1630.78  4877.8 1630.36  4898.9  1630.5    4908  1629.9  4944.1 1628.71
  4980.3 1628.74  4986.3 1628.38  4994.1 1626.21  4997.5 1625.81    4998 1625.31
  5004.6 1625.31  5005.1 1625.81  5016.4  1626.2  5043.5 1628.25  5101.9 1628.08
    5161 1628.51  5209.6 1629.32  5218.2 1628.69  5224.2  1629.1  5239.3 1628.88
  5245.5 1628.22  5269.4 1628.19  5413.1 1630.29  5456.2 1630.14  5618.2 1630.71
#Mann= 3 ,-1 , 0
  4659.3     .05       0  4997.5     .05       0  5005.1     .05       0
Bank Sta=4997.5,5005.1
XS Rating Curve= 0 ,0
Exp/Cntr=0.3,0.1

Type RM Length L Ch R = 1 ,27617   ,316,316,316
BEGIN DESCRIPTION:
Mapping XS 71541e72
END DESCRIPTION:
XS GIS Cut Line= 2
      1598055.72      6948512.07      1597697.51      6947687.52
#Sta/Elev= 30
  4601.3 1631.15  4660.3 1630.36  4736.1 1628.43  4770.5 1628.44  4788.5 1627.41
  4823.8 1626.84  4846.3 1626.87  4900.1 1625.95    4911 1626.28  4945.6 1626.23
  4954.6 1625.25  4963.6 1625.13    4969 1626.01  4998.2 1625.66  5009.1 1625.01
  5012.1 1622.62  5012.6 1622.12  5019.2 1622.12  5019.7 1622.62  5021.4 1623.54
    5031 1623.17  5039.4 1625.27  5044.8 1623.01  5052.8 1624.95  5062.8 1625.65
  5074.6 1625.34  5205.4 1625.79  5303.5 1627.28  5394.9 1627.61  5500.3 1627.39
#Mann= 3 ,-1 , 0
  4601.3     .05       0  5012.1     .05       0  5019.7     .05       0
Bank Sta=5012.1,5019.7
XS Rating Curve= 0 ,0
Exp/Cntr=0.3,0.1

Type RM Length L Ch R = 1 ,27301   ,397,397,397
BEGIN DESCRIPTION:
Mapping XS 6f44eaf5
END DESCRIPTION:
XS GIS Cut Line= 2
       1598269.4      6948474.12      1598079.98       6947543.5
#Sta/Elev= 30
  4605.8 1627.84  4714.1 1626.48  4785.5 1624.66  4807.2 1625.31  4836.6 1624.25
  4857.8 1624.51  4867.2 1623.66  4897.8 1623.97  4908.4 1624.75  4928.4 1624.64
  4938.6 1624.11  4948.7  1624.7  4999.3 1623.46  5004.4 1622.95  5006.2 1620.88
  5006.7 1620.38  5013.4 1620.38  5013.9 1620.88  5020.2 1622.12  5030.5  1622.8
  5040.7 1624.63  5061.1 1623.85  5091.7  1624.3  5112.1 1623.82  5156.2    1624
  5224.3 1623.04  5409.1 1624.93  5448.9 1624.57  5489.7 1624.86  5555.5  1625.8
#Mann= 3 ,-1 , 0
  4605.8     .05       0  5006.2     .05       0  5013.9     .05       0
Bank Sta=5006.2,5013.9
XS Rating Curve= 0 ,0
Exp/Cntr=0.3,0.1

Type RM Length L Ch R = 1 ,26904   ,89,89,89
BEGIN DESCRIPTION:
Mapping XS b6f15bfd
END DESCRIPTION:
XS GIS Cut Line= 4
      1598555.92      6948562.85      1598539.02      6948028.83
       1598542.4      6947829.43      1598528.84      6947267.51
#Sta/Elev= 30
  4525.4 1623.24  4830.4  1621.7  4860.4 1622.24  4930.5 1622.34  4970.5 1623.31
  5000.5 1621.02  5020.5 1624.96  5027.2 1625.34  5032.2 1624.14  5050.5  1621.7
  5080.5 1619.93  5100.5 1620.99  5110.5 1622.73  5121.4    1626  5140.5  1627.1
  5160.5 1621.92  5170.5 1621.54  5176.6 1618.84  5177.1 1618.34    5184 1618.34
  5184.5 1618.84  5190.5 1619.99  5230.5 1621.75  5250.5 1621.09  5270.6 1621.92
  5310.6 1621.39  5370.6  1622.2  5470.6 1622.13  5500.6 1621.62  5821.2 1623.72
#Mann= 3 ,-1 , 0
  4525.4     .05       0  5176.6     .03       0  5184.5     .05       0
Bank Sta=5176.6,5184.5
XS Rating Curve= 0 ,0
Exp/Cntr=0.3,0.1

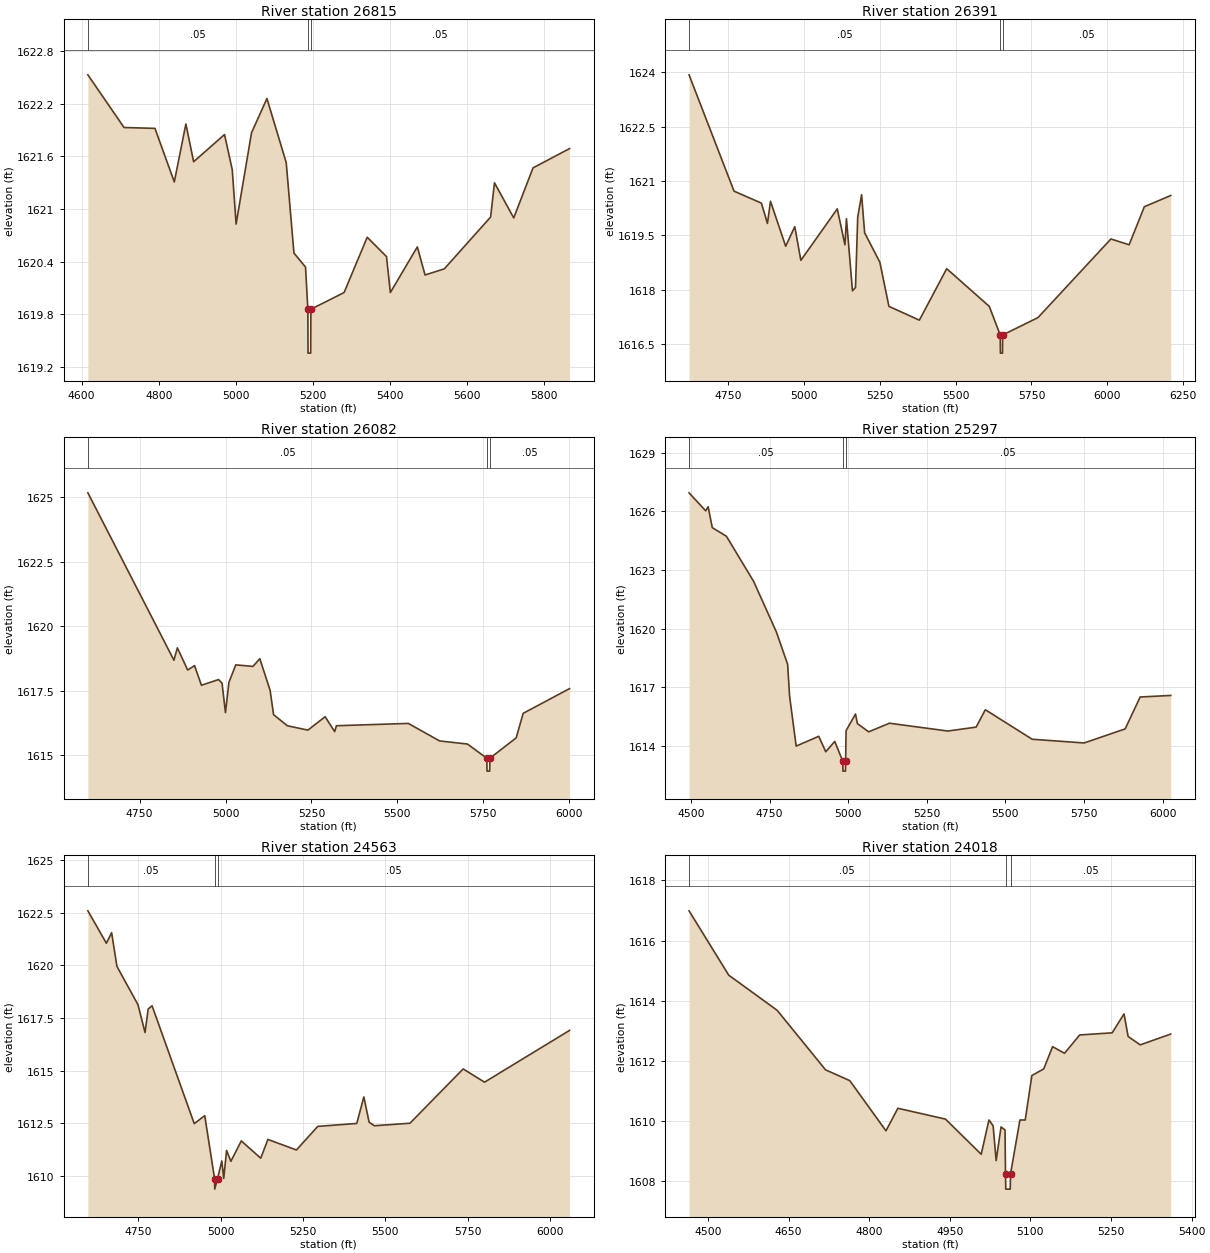
Type RM Length L Ch R = 1 ,26815   ,424,424,424
BEGIN DESCRIPTION:
Mapping XS bdfac55e
END DESCRIPTION:
XS GIS Cut Line= 4
      1598657.31      6948471.54      1598630.27      6948106.56
      1598626.89      6947795.63      1598640.01      6947223.21
#Sta/Elev= 30
  4616.2 1622.53    4710 1621.93  4790.2 1621.92  4840.4 1621.31  4870.4 1621.97
  4890.5 1621.54  4970.7 1621.85  4990.7 1621.45  5000.7 1620.83  5040.7 1621.87
  5080.7 1622.26  5130.7 1621.53  5150.7  1620.5  5180.8 1620.34  5186.8 1619.86
  5187.3 1619.36  5194.2 1619.36  5194.7 1619.86  5280.8 1620.05  5340.8 1620.68
  5390.8 1620.46  5400.8 1620.05  5470.8 1620.57  5490.8 1620.25  5540.8 1620.32
  5660.9 1620.91  5670.9  1621.3  5720.9  1620.9  5770.9 1621.47  5865.7 1621.69
#Mann= 3 ,-1 , 0
  4616.2     .05       0  5186.8     .03       0  5194.7     .05       0
Bank Sta=5186.8,5194.7
XS Rating Curve= 0 ,0
Exp/Cntr=0.3,0.1

Type RM Length L Ch R = 1 ,26391   ,309,309,309
BEGIN DESCRIPTION:
Mapping XS 6ff5a1f0
END DESCRIPTION:
XS GIS Cut Line= 3
      1599032.45      6948566.18      1599018.93      6948008.55
      1598961.35      6946981.16
#Sta/Elev= 30
  4622.1 1623.93  4770.3 1620.72  4860.4 1620.39  4880.4 1619.83  4890.4 1620.44
  4940.4  1619.2  4970.4 1619.74  4990.4 1618.81  5110.4 1620.23  5135.6 1619.24
  5140.6 1619.96  5160.4 1617.97  5170.4 1618.06  5177.7    1620  5190.5 1620.62
  5200.5 1619.57  5250.6 1618.76  5280.6 1617.54  5380.8 1617.16  5470.9 1618.58
  5611.1 1617.54  5647.2 1616.75  5647.7 1616.25  5654.6 1616.25  5655.1 1616.75
  5771.4 1617.23  6011.8  1619.4  6071.8 1619.24  6121.9 1620.29  6208.9  1620.6
#Mann= 3 ,-1 , 0
  4622.1     .05       0  5647.2     .05       0  5655.1     .05       0
Bank Sta=5647.2,5655.1
XS Rating Curve= 0 ,0
Exp/Cntr=0.3,0.1

Type RM Length L Ch R = 1 ,26082   ,785,785,785
BEGIN DESCRIPTION:
Mapping XS 76fb0c02
END DESCRIPTION:
XS GIS Cut Line= 3
      1599302.82      6948488.45       1599289.3      6947728.04
      1599187.74      6947094.56
#Sta/Elev= 30
  4599.2 1625.17  4849.7 1618.68  4859.7 1619.16  4889.7  1618.3  4909.7 1618.47
  4929.7 1617.71  4979.7 1617.93  4989.7 1617.79  4999.7 1616.65  5009.7 1617.82
  5029.7  1618.5  5079.7 1618.44  5099.7 1618.74  5129.7 1617.51  5139.7 1616.57
  5179.7 1616.14  5239.8 1615.97  5289.8 1616.49  5317.6 1615.91  5322.6 1616.14
  5531.9 1616.23  5623.1 1615.55  5704.1 1615.43  5760.5 1614.88    5761 1614.38
  5768.8 1614.38  5769.3 1614.88  5845.9 1615.67  5866.2 1616.62  6001.3 1617.58
#Mann= 3 ,-1 , 0
  4599.2     .05       0  5760.5     .05       0  5769.3     .05       0
Bank Sta=5760.5,5769.3
XS Rating Curve= 0 ,0
Exp/Cntr=0.3,0.1

Type RM Length L Ch R = 1 ,25297   ,734,734,734
BEGIN DESCRIPTION:
Mapping XS 3bc6f327
END DESCRIPTION:
XS GIS Cut Line= 3
      1600215.33      6948231.61      1599607.82       6947821.4
       1599303.2      6947082.57
#Sta/Elev= 30
  4493.7 1626.95  4546.6 1626.03  4554.4 1626.24  4567.6 1625.17  4612.5 1624.73
  4699.2 1622.42  4771.4 1619.84  4807.3 1618.18  4813.4 1616.57  4834.4    1614
  4906.3  1614.5  4928.5 1613.71  4957.2 1614.24  4982.7 1613.22  4983.2 1612.72
  4991.2 1612.72  4991.7 1613.22  4993.2 1614.79  5023.1 1615.64  5029.2 1615.15
  5065.1 1614.73  5131.1 1615.17  5316.9 1614.77  5406.8 1614.97  5436.1 1615.86
  5585.1 1614.35  5750.4 1614.16  5880.9 1614.88  5928.7 1616.51  6025.9 1616.59
#Mann= 3 ,-1 , 0
  4493.7     .05       0  4982.7     .05       0  4991.7     .05       0
Bank Sta=4982.7,4991.7
XS Rating Curve= 0 ,0
Exp/Cntr=0.3,0.1

Type RM Length L Ch R = 1 ,24563   ,545,545,545
BEGIN DESCRIPTION:
Mapping XS 298414b9
END DESCRIPTION:
XS GIS Cut Line= 3
      1600627.67      6947728.05      1600262.63      6947592.86
        1599330.        6947063.
#Sta/Elev= 30
  4597.1 1622.59  4653.3 1621.05  4669.2 1621.55  4685.3 1619.95  4749.2 1618.13
  4770.6 1616.81  4780.2 1617.93  4791.9 1618.08  4919.9 1612.48  4951.8 1612.86
  4981.6 1609.87  4982.1 1609.37  4990.7 1609.87  5003.6 1610.71  5009.4 1609.88
  5018.1 1611.21    5031 1610.69  5062.7 1611.66  5121.7 1610.84  5143.5 1611.73
    5230 1611.23  5294.8 1612.35  5413.1 1612.49  5434.7 1613.75  5450.6 1612.55
  5466.4 1612.38  5574.6  1612.5    5736 1615.08  5800.9 1614.45    6059 1616.91
#Mann= 3 ,-1 , 0
  4597.1     .05       0  4981.6     .05       0  4990.7     .05       0
Bank Sta=4981.6,4990.7
XS Rating Curve= 0 ,0
Exp/Cntr=0.3,0.1

Type RM Length L Ch R = 1 ,24018   ,533,533,533
BEGIN DESCRIPTION:
Mapping XS 495d3da6
END DESCRIPTION:
XS GIS Cut Line= 2
      1600600.57      6947413.72      1599804.54      6947002.22
#Sta/Elev= 30
    4465 1616.99  4538.8 1614.85  4628.9 1613.68  4718.9  1611.7    4764 1611.34
  4831.3 1609.67  4853.5 1610.42    4942 1610.06  5008.5 1608.89  5022.9 1610.03
  5030.6 1609.84  5036.3 1608.68  5045.4  1609.8  5052.8  1609.7  5053.7 1608.23
  5054.2 1607.73  5062.5 1607.73    5063 1608.23  5080.5 1610.03  5090.4 1610.03
  5102.7 1611.51  5124.8 1611.73  5141.3 1612.47  5163.5 1612.25  5191.7 1612.86
  5252.1 1612.93  5274.2 1613.56  5281.8 1612.81  5304.3 1612.53  5361.1 1612.89
#Mann= 3 ,-1 , 0
    4465     .05       0  5053.7     .05       0    5063     .05       0
Bank Sta=5053.7,5063
XS Rating Curve= 0 ,0
Exp/Cntr=0.3,0.1

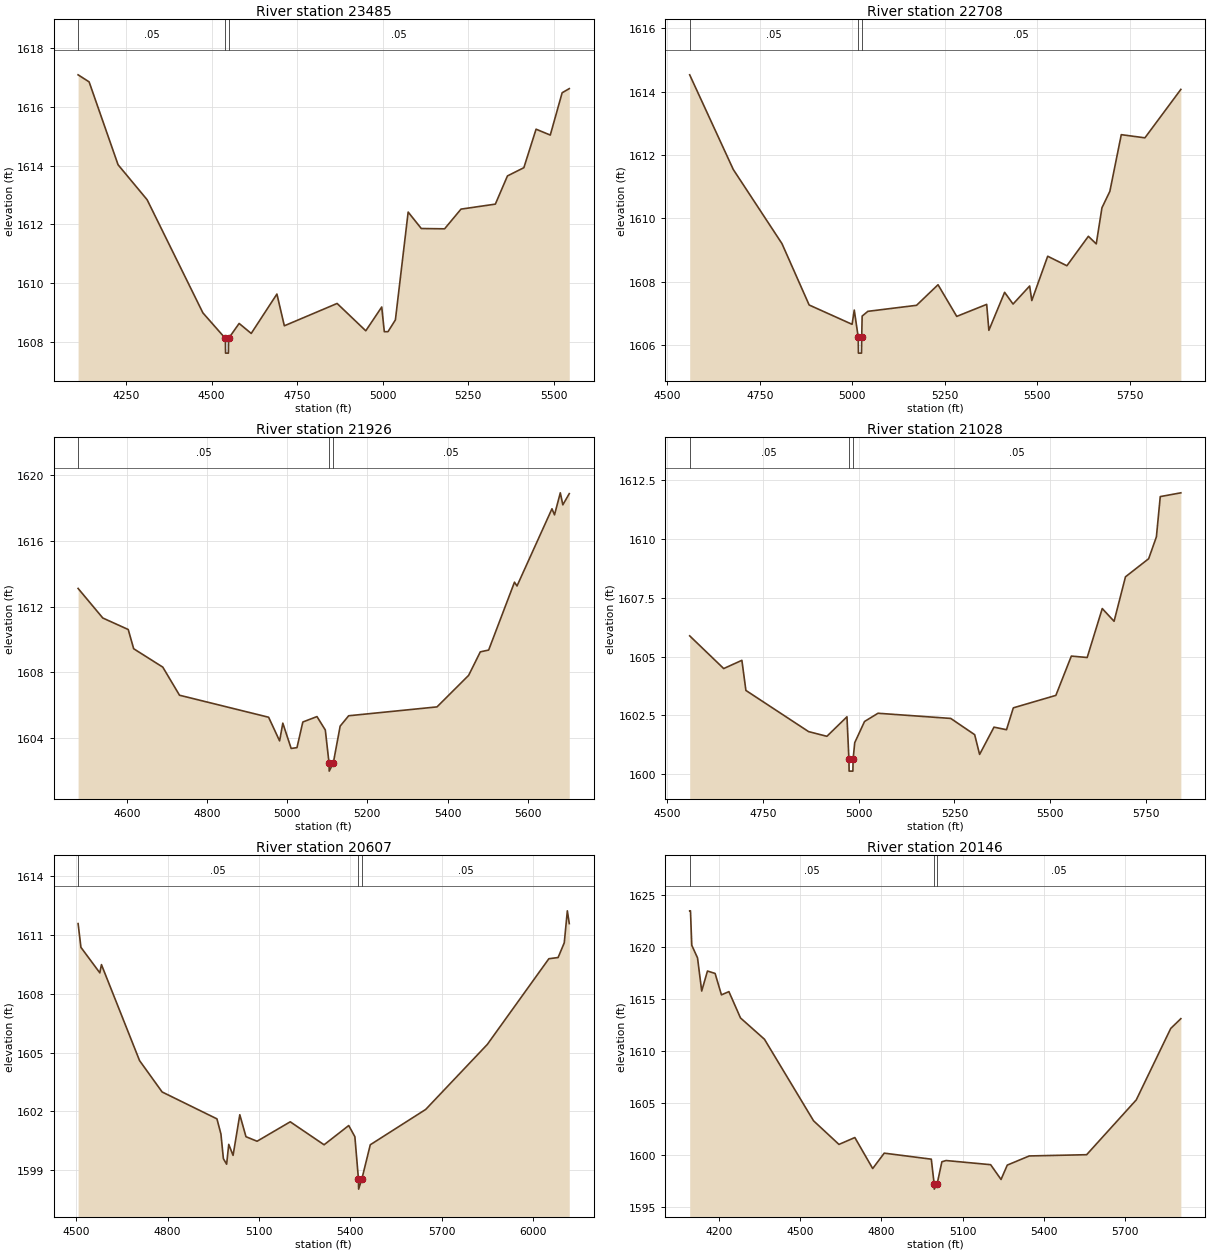
Type RM Length L Ch R = 1 ,23485   ,777,777,777
BEGIN DESCRIPTION:
Mapping XS fd83ad1f
END DESCRIPTION:
XS GIS Cut Line= 3
      1600708.78      6947349.55      1600336.98      6946994.66
      1599485.34      6946643.19
#Sta/Elev= 30
    4110 1617.09  4142.2 1616.85  4226.8 1614.03  4311.7 1612.84  4474.7 1608.99
  4540.4 1608.12  4540.9 1607.62  4549.2 1607.62  4549.7 1608.12  4580.6 1608.63
  4615.9 1608.29    4691 1609.63  4712.7 1608.55  4866.9 1609.31  4950.7 1608.38
  4997.3 1609.19  5004.8 1608.35  5015.6 1608.35  5037.2 1608.75  5074.5 1612.42
  5112.9 1611.86    5181 1611.85  5228.9 1612.52  5329.3 1612.69  5364.7 1613.65
  5412.6 1613.93  5448.3 1615.24  5489.8 1615.04  5524.5 1616.48  5545.3 1616.62
#Mann= 3 ,-1 , 0
    4110     .05       0  4540.4     .05       0  4549.7     .05       0
Bank Sta=4540.4,4549.7
XS Rating Curve= 0 ,0
Exp/Cntr=0.3,0.1

Type RM Length L Ch R = 1 ,22708   ,782,782,782
BEGIN DESCRIPTION:
Mapping XS 6a6bf8fa
END DESCRIPTION:
XS GIS Cut Line= 2
      1600911.54      6946933.84      1599777.63      6946242.02
#Sta/Elev= 30
  4560.4 1614.53  4678.3 1611.54  4809.9  1609.2  4883.5 1607.26  4999.6 1606.65
  5005.5  1607.1  5016.2 1606.24  5016.7 1605.74  5025.1 1605.74  5025.6 1606.24
  5026.8 1606.91  5042.3 1607.06  5173.9 1607.25    5232  1607.9  5282.6  1606.9
  5363.6 1607.28  5369.5 1606.46  5412.1 1607.66  5434.9 1607.29  5479.8 1607.86
  5485.6  1607.4  5528.6  1608.8  5580.5  1608.5  5638.6 1609.43  5659.9 1609.19
  5675.3 1610.33  5696.7 1610.85  5727.6 1612.64  5791.5 1612.54  5888.7 1614.07
#Mann= 3 ,-1 , 0
  4560.4     .05       0  5016.2     .05       0  5025.6     .05       0
Bank Sta=5016.2,5025.6
XS Rating Curve= 0 ,0
Exp/Cntr=0.3,0.1

Type RM Length L Ch R = 1 ,21926   ,898,898,898
BEGIN DESCRIPTION:
Mapping XS 91b51c6e
END DESCRIPTION:
XS GIS Cut Line= 2
      1601114.31      6946453.93        1600141.      6945710.43
#Sta/Elev= 30
  4478.8 1613.11  4540.4 1611.31  4603.8 1610.61  4617.4 1609.44    4690 1608.32
  4731.7 1606.61  4953.9 1605.27  4981.3 1603.83  4989.3 1604.91  5010.1 1603.37
  5024.6 1603.42  5039.2 1604.98  5074.5 1605.31  5095.3 1604.49  5104.5 1602.49
    5105 1601.99  5115.2 1602.49  5132.3 1604.73  5153.5 1605.36  5373.8  1605.9
  5452.7 1607.82  5481.8 1609.25  5502.6 1609.36    5567 1613.49  5573.3 1613.26
  5660.5 1617.96  5666.8 1617.59  5681.3 1618.93  5687.6  1618.2  5703.6 1618.88
#Mann= 3 ,-1 , 0
  4478.8     .05       0  5104.5     .05       0  5115.2     .05       0
Bank Sta=5104.5,5115.2
XS Rating Curve= 0 ,0
Exp/Cntr=0.3,0.1

Type RM Length L Ch R = 1 ,21028   ,421,421,421
BEGIN DESCRIPTION:
Mapping XS c5cb1baf
END DESCRIPTION:
XS GIS Cut Line= 3
      1601469.11      6945598.87      1601019.67      6945515.68
      1600201.75      6945397.39
#Sta/Elev= 30
  4558.2 1605.88  4647.1 1604.49  4694.6 1604.84  4705.1 1603.56  4868.9 1601.81
  4916.7 1601.61  4969.2 1602.44  4974.3 1600.63  4974.8 1600.13  4984.7 1600.13
  4985.2 1600.63  4989.5 1601.34  5015.1 1602.24  5050.3 1602.59  5240.4 1602.37
  5302.9 1601.68  5315.8 1600.84  5353.4    1602  5386.1 1601.89  5403.9 1602.82
  5515.1 1603.35  5555.5 1605.02  5596.9 1604.96  5636.3 1607.04  5667.2  1606.5
    5697 1608.39  5757.6 1609.16  5777.8 1610.09  5787.9  1611.8  5841.7 1611.96
#Mann= 3 ,-1 , 0
  4558.2     .05       0  4974.3     .05       0  4985.2     .05       0
Bank Sta=4974.3,4985.2
XS Rating Curve= 0 ,0
Exp/Cntr=0.3,0.1

Type RM Length L Ch R = 1 ,20607   ,461,461,461
BEGIN DESCRIPTION:
Mapping XS 4592e3fc
END DESCRIPTION:
XS GIS Cut Line= 3
       1601695.6      6945477.21       1601097.4      6945267.67
      1600128.75      6945119.17
#Sta/Elev= 30
  4505.9 1611.57  4515.2 1610.36  4577.3 1609.06  4582.6 1609.48  4707.8 1604.59
    4782 1602.99  4962.1 1601.62  4975.2 1600.85  4983.3 1599.59  4993.9 1599.31
  5000.9 1600.32  5015.1 1599.76  5037.2 1601.83  5057.5 1600.71    5094 1600.48
  5202.9 1601.47  5314.1  1600.3  5395.1 1601.28  5415.3 1600.71  5427.1 1598.54
  5427.6 1598.04    5438 1598.54  5465.9  1600.3    5648  1602.1  5850.3 1605.41
  6052.7 1609.78    6083 1609.84  6103.3 1610.59  6113.4 1612.22  6119.7 1611.57
#Mann= 3 ,-1 , 0
  4505.9     .05       0  5427.1     .05       0    5438     .05       0
Bank Sta=5427.1,5438
XS Rating Curve= 0 ,0
Exp/Cntr=0.3,0.1

Type RM Length L Ch R = 1 ,20146   ,311,311,311
BEGIN DESCRIPTION:
Deadman 02 32.0
END DESCRIPTION:
XS GIS Cut Line= 3
      1601955.01        6945438.      1601188.65      6944966.89
        1600355.        6944588.
#Sta/Elev= 30
  4091.5 1623.49  4094.4 1623.49  4099.2 1620.18  4120.5 1618.96  4135.9 1615.78
  4157.2  1617.7  4185.4 1617.47  4208.9 1615.41  4236.5 1615.72  4279.3 1613.19
  4367.9 1611.14  4549.3  1603.3  4643.2 1601.03  4701.9 1601.69  4767.9 1598.71
  4810.5 1600.19  4984.5 1599.61    4995 1597.23  4995.5 1596.73    5006 1597.23
  5023.6 1599.36    5039 1599.48  5203.8 1599.08  5242.2 1597.66  5265.3 1599.04
  5346.6 1599.92  5558.6 1600.04    5742 1605.31  5869.4 1612.18  5906.8 1613.12
#Mann= 3 ,-1 , 0
  4091.5     .05       0    4995     .05       0    5006     .05       0
Bank Sta=4995,5006
XS Rating Curve= 0 ,0
Exp/Cntr=0.3,0.1

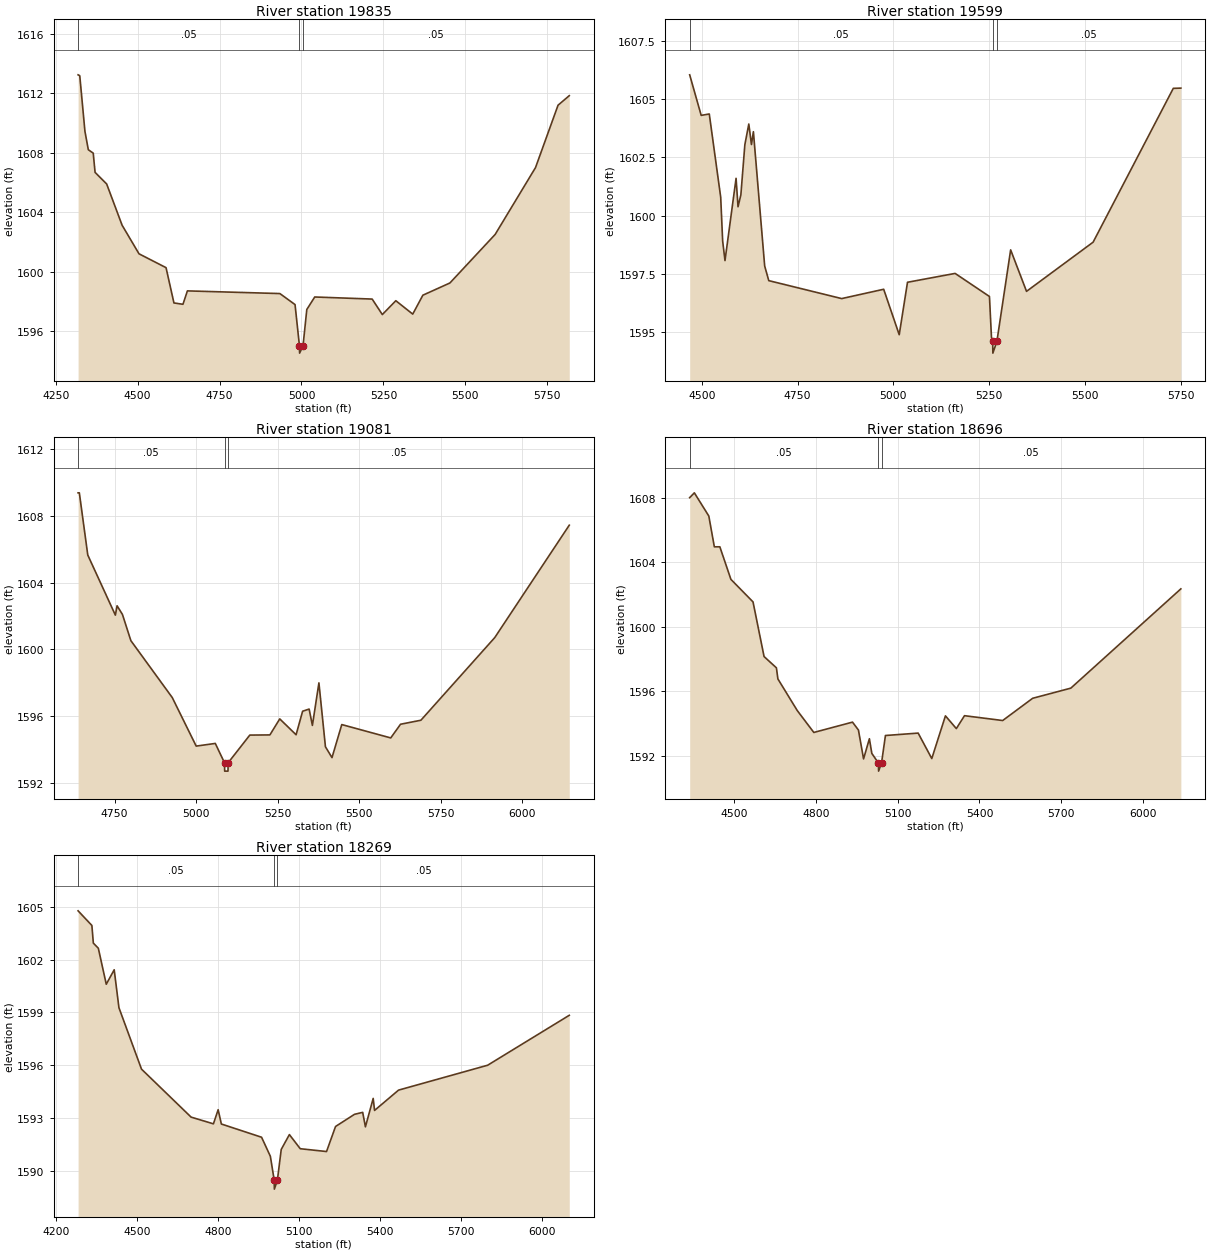
Type RM Length L Ch R = 1 ,19835   ,236,236,236
BEGIN DESCRIPTION:
Mapping XS b142fc7e
END DESCRIPTION:
XS GIS Cut Line= 2
      1601865.25      6944854.17      1600411.82      6944487.37
#Sta/Elev= 30
  4318.3 1613.23  4323.4 1613.17  4339.2 1609.43  4349.5  1608.2  4364.5 1607.97
  4370.1 1606.68  4405.5  1605.9  4452.6 1603.13  4504.2 1601.21  4586.7 1600.28
  4610.8 1597.91  4638.3 1597.82  4651.9 1598.72  4934.1 1598.54  4980.4  1597.8
  4993.8 1595.04  4994.3 1594.54  5004.8 1595.04  5016.3 1597.47  5040.5 1598.31
  5215.8 1598.17  5246.8 1597.13    5288 1598.06  5339.6 1597.16  5370.5 1598.43
    5453 1599.25  5591.1 1602.51  5714.3    1607  5783.1 1611.19  5817.3 1611.83
#Mann= 3 ,-1 , 0
  4318.3     .05       0  4993.8     .05       0  5004.8     .05       0
Bank Sta=4993.8,5004.8
XS Rating Curve= 0 ,0
Exp/Cntr=0.3,0.1

Type RM Length L Ch R = 1 ,19599   ,518,518,518
BEGIN DESCRIPTION:
Mapping XS f5a90c2c
END DESCRIPTION:
XS GIS Cut Line= 2
      1601824.03      6944624.93      1600585.99      6944294.78
#Sta/Elev= 30
  4468.6 1606.04  4498.6  1604.3  4519.7 1604.36  4549.5 1600.79  4554.6 1598.91
  4560.7 1598.07  4589.6  1601.6  4594.7 1600.38  4602.1 1600.89  4612.5 1603.04
  4622.8 1603.93  4629.7 1603.05  4634.8  1603.6  4664.2 1597.84  4674.9 1597.21
  4865.1 1596.44  4974.7 1596.84  5015.2 1594.89  5036.8 1597.14    5161 1597.52
  5250.6 1596.53  5255.8 1594.79    5259  1594.6  5259.5  1594.1    5270  1594.6
  5305.9 1598.53  5347.3 1596.75    5521 1598.86  5730.2 1605.46  5749.9 1605.47
#Mann= 3 ,-1 , 0
  4468.6     .05       0    5259     .03       0    5270     .05       0
Bank Sta=5259,5270
XS Rating Curve= 0 ,0
Exp/Cntr=0.3,0.1

Type RM Length L Ch R = 1 ,19081   ,385,385,385
BEGIN DESCRIPTION:
Mapping XS 8a35169a
END DESCRIPTION:
XS GIS Cut Line= 3
      1602007.37       6944290.2      1601428.52      6944153.48
      1600518.14      6944192.68
#Sta/Elev= 30
  4637.9 1609.38  4641.7 1609.38  4667.6 1605.65  4752.2 1602.05  4757.4 1602.61
  4773.9 1602.09  4799.7 1600.52  4926.6 1597.11    5000  1594.2  5058.6 1594.36
  5086.8  1593.2  5087.3  1592.7  5097.5  1592.7    5098  1593.2  5164.4 1594.86
    5226 1594.87  5256.2 1595.83  5306.3 1594.88  5326.3 1596.29  5346.3 1596.42
  5356.3 1595.44  5376.3 1597.99  5396.3 1594.16  5416.4 1593.51  5446.4 1595.49
  5596.5 1594.69  5626.6 1595.51    5689 1595.75  5915.3  1600.7  6143.9 1607.44
#Mann= 3 ,-1 , 0
  4637.9     .05       0  5086.8     .05       0    5098     .05       0
Bank Sta=5086.8,5098
XS Rating Curve= 0 ,0
Exp/Cntr=0.3,0.1

Type RM Length L Ch R = 1 ,18696   ,427,427,427
BEGIN DESCRIPTION:
Mapping XS f0c6221c
END DESCRIPTION:
XS GIS Cut Line= 3
      1602264.17      6943946.34      1601617.66      6943836.29
      1600471.41      6943795.03
#Sta/Elev= 30
  4336.3 1608.02  4353.4 1608.32  4406.5 1606.88  4426.8 1604.97    4447 1604.97
  4487.6 1602.95  4568.8 1601.55  4609.3 1598.16  4654.6 1597.46  4660.1 1596.77
  4731.1 1594.81  4791.9 1593.45  4933.9 1594.09  4955.7  1593.6  4974.5 1591.81
  4995.9 1593.06  5004.8 1592.15  5029.2 1591.55  5029.7 1591.05  5040.4 1591.55
  5054.8 1593.26  5174.9 1593.41  5224.9 1591.83    5275 1594.48    5315 1593.69
    5345 1594.49  5485.1 1594.19  5595.2 1595.57  5735.3  1596.2  6139.1 1602.36
#Mann= 3 ,-1 , 0
  4336.3     .05       0  5029.2     .05       0  5040.4     .05       0
Bank Sta=5029.2,5040.4
XS Rating Curve= 0 ,0
Exp/Cntr=0.3,0.1

Type RM Length L Ch R = 1 ,18269   ,467,467,467
BEGIN DESCRIPTION:
Mapping XS 1cee4d2d
END DESCRIPTION:
XS GIS Cut Line= 3
      1602365.04      6943703.34      1601718.53      6943437.39
      1600604.38      6943565.77
#Sta/Elev= 30
    4281 1604.76  4332.1 1603.93  4337.5 1602.93    4356 1602.64  4385.4  1600.6
  4414.8 1601.42  4432.4 1599.27    4516 1595.79  4699.9 1593.07  4782.6 1592.69
  4800.1 1593.49    4812 1592.68  4961.1 1591.93  4993.7 1590.85    5008 1589.49
  5008.5 1588.99  5019.6 1589.49    5034 1591.24  5064.2 1592.08  5104.4 1591.28
  5201.9 1591.12  5235.3 1592.54  5305.7 1593.23  5335.9 1593.34    5346 1592.52
  5374.8 1594.13  5379.9 1593.45  5468.8  1594.6    5799 1596.01  6101.6 1598.84
#Mann= 3 ,-1 , 0
    4281     .05       0    5008     .05       0  5019.6     .05       0
Bank Sta=5008,5019.6
XS Rating Curve= 0 ,0
Exp/Cntr=0.3,0.1