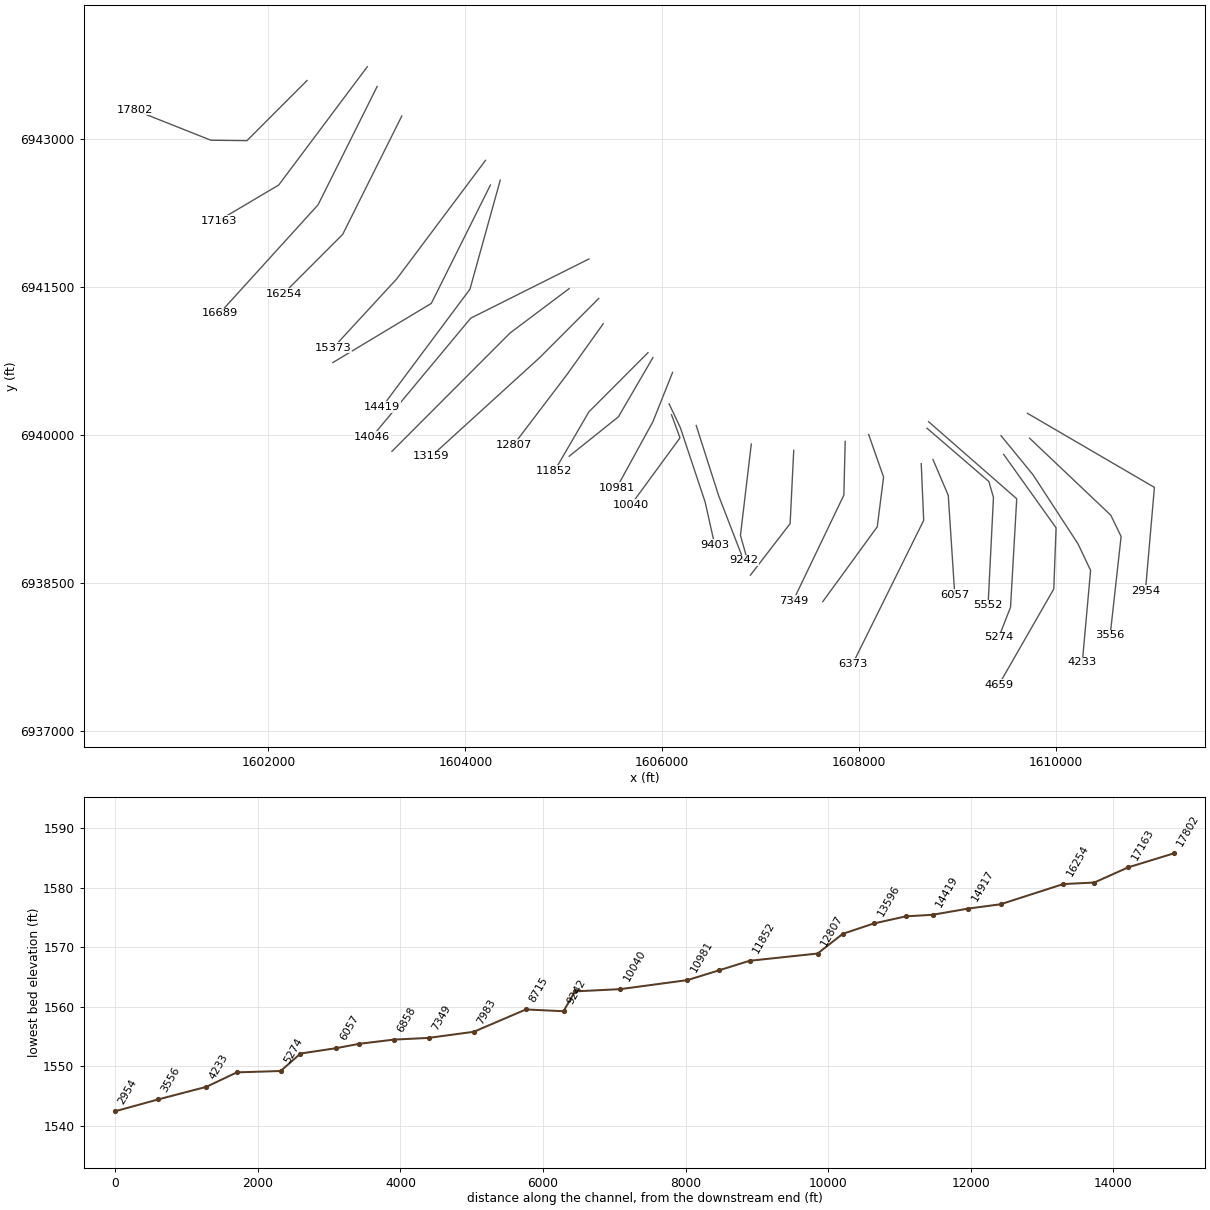
HEC-RAS study Deadman 02.prj: Deadman 02 Base Level Engineering

--- Deadman 02.g01 (geometry) --- (continued)

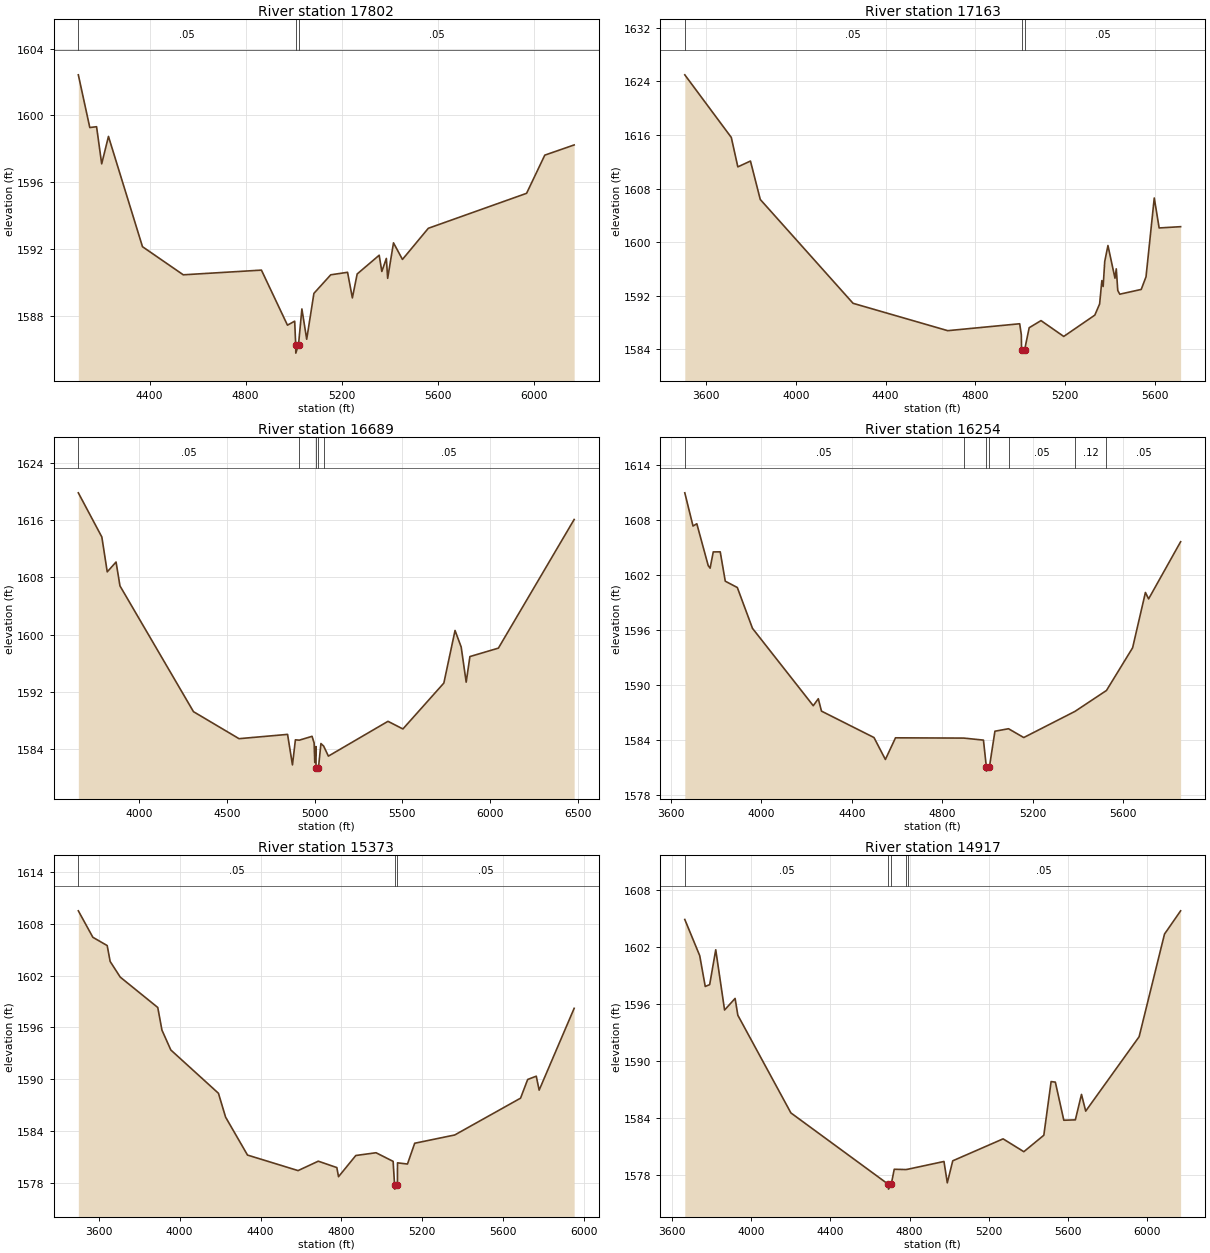
Type RM Length L Ch R = 1 ,17802   ,639,639,639
BEGIN DESCRIPTION:
Mapping XS cc234db8
END DESCRIPTION:
XS GIS Cut Line= 4
      1602392.53      6943597.87      1601782.72      6942988.06
      1601415.92      6942992.65      1600641.02      6943299.85
#Sta/Elev= 30
  4103.9 1602.43  4151.6 1599.28  4179.8 1599.33  4201.1 1597.11  4229.3 1598.75
  4370.8 1592.16  4540.5 1590.48  4865.7 1590.76    4974 1587.47    5004 1587.71
  5008.2  1586.3  5008.7  1585.8  5019.9  1586.3    5034 1588.44    5054 1586.63
    5084 1589.37    5154 1590.48    5224 1590.63    5244  1589.1    5264 1590.53
  5355.6 1591.65  5366.5 1590.68  5385.4 1591.46  5390.8 1590.27  5415.1 1592.39
  5452.4  1591.4    5560 1593.26  5968.8 1595.35  6044.5 1597.63  6166.7 1598.24
#Mann= 3 ,-1 , 0
  4103.9     .05       0  5008.2     .05       0  5019.9     .05       0
Bank Sta=5008.2,5019.9
XS Rating Curve= 0 ,0
Exp/Cntr=0.3,0.1

Type RM Length L Ch R = 1 ,17163   ,474,474,474
BEGIN DESCRIPTION:
Deadman 02 27.0
END DESCRIPTION:
XS GIS Cut Line= 3
      1603004.99      6943737.99        1602105.        6942538.
      1601493.89      6942176.53
#Sta/Elev= 30
  3504.9 1624.96  3712.2 1615.62  3741.3 1611.23  3797.6  1612.1  3841.3 1606.37
  4254.9 1590.88  4676.8  1586.8  4997.6 1587.83  5004.9 1586.18  5005.9 1583.95
  5006.4 1583.45  5019.6 1583.95  5039.9 1587.24  5092.6  1588.3    5194 1585.94
  5332.5 1589.12  5353.9 1590.79  5363.8 1594.27  5369.6 1593.39  5376.7 1597.13
    5391  1599.5  5422.3 1594.63  5428.1 1596.02  5434.8 1592.79  5443.7 1592.24
  5539.3 1592.95  5560.7 1594.84  5597.4 1606.59  5619.2 1602.12  5714.9 1602.31
#Mann= 3 ,-1 , 0
  3504.9     .05       0  5005.9     .05       0  5019.6     .05       0
Bank Sta=5005.9,5019.6
XS Rating Curve= 0 ,0
Exp/Cntr=0.3,0.1

Type RM Length L Ch R = 1 ,16689   ,435,435,435
BEGIN DESCRIPTION:
Deadman 02 26.0
END DESCRIPTION:
XS GIS Cut Line= 3
      1603104.98      6943537.96        1602505.        6942338.
        1601505.        6941238.
#Sta/Elev= 30
    3652 1619.84  3786.1 1613.66  3816.9 1608.78  3867.2 1610.16  3889.5 1606.82
  4308.8 1589.22  4568.7 1585.44  4845.5 1586.04  4873.4 1581.77  4890.2 1585.28
  4912.4 1585.23  4985.2 1585.77    4997 1584.84  5000.7  1582.1  5007.5 1584.34
  5007.9  1581.4  5008.4  1580.9  5021.9  1581.4  5035.8 1584.76  5051.4  1584.4
  5078.4    1583  5418.3 1587.87  5503.4  1586.8  5736.9 1593.22  5800.8 1600.58
  5835.9 1598.26  5864.3 1593.35  5885.6 1596.93  6048.1 1598.11  6480.2 1616.11
#Mann= 5 ,-1 , 0
    3652     .05       0  4912.4     .12       0  5007.9     .05       0
  5021.9     .12       0  5051.4     .05       0
Bank Sta=5007.9,5021.9
XS Rating Curve= 0 ,0
Exp/Cntr=0.3,0.1

Type RM Length L Ch R = 1 ,16254   ,881,881,881
BEGIN DESCRIPTION:
Deadman 02 25.0
END DESCRIPTION:
XS GIS Cut Line= 3
      1603354.98      6943237.96        1602755.        6942038.
      1602155.02      6941438.02
#Sta/Elev= 30
  3662.7 1610.97    3699 1607.35  3715.8  1607.6  3766.1 1603.04  3774.5 1602.76
  3788.4 1604.53  3819.2 1604.54  3841.5 1601.34  3894.7 1600.65  3961.7  1596.2
  4230.1 1587.77  4252.4 1588.53  4266.4 1587.18  4498.4  1584.3  4548.7 1581.91
  4593.4 1584.27  4894.9 1584.24  4981.9 1584.02  4994.5 1581.14    4995 1580.64
  5008.5 1581.14  5032.6 1584.99  5092.6 1585.26  5159.9  1584.3  5386.1 1587.15
  5525.3 1589.43  5640.7 1594.08  5697.3 1600.11  5711.4 1599.41  5852.8 1605.64
#Mann= 7 ,-1 , 0
  3662.7     .05       0  4894.9     .12       0  4994.5     .05       0
  5008.5     .12       0  5092.6     .05       0  5386.1     .12       0
  5525.3     .05       0
Bank Sta=4994.5,5008.5
XS Rating Curve= 0 ,0
Exp/Cntr=0.3,0.1

Type RM Length L Ch R = 1 ,15373   ,456,456,456
BEGIN DESCRIPTION:
Deadman 02 24.0
END DESCRIPTION:
XS GIS Cut Line= 3
      1604204.99      6942787.99        1603305.        6941588.
      1602659.65      6940888.93
#Sta/Elev= 30
  3499.1 1609.52    3571 1606.45  3641.8 1605.49  3656.4 1603.65  3706.4 1601.83
  3891.8 1598.31  3912.6 1595.68  3956.4 1593.38  4191.8 1588.36  4227.2 1585.59
  4335.5 1581.19  4585.5 1579.39  4685.5 1580.48  4777.2 1579.74  4785.5 1578.68
    4871 1581.14    4971 1581.46  5055.5 1580.46  5062.6 1577.74  5063.1 1577.24
  5076.8 1577.74  5077.1 1580.29  5126.4 1580.15  5162.1 1582.56    5360 1583.52
  5685.5 1587.79  5720.7 1589.96  5763.2 1590.34  5777.4 1588.72  5950.5 1598.21
#Mann= 3 ,-1 , 0
  3499.1     .05       0  5062.6     .03       0  5076.8     .05       0
Bank Sta=5062.6,5076.8
XS Rating Curve= 0 ,0
Exp/Cntr=0.3,0.1

Type RM Length L Ch R = 1 ,14917   ,498,498,498
BEGIN DESCRIPTION:
Deadman 02 23.0
END DESCRIPTION:
XS GIS Cut Line= 3
        1604255.        6942538.        1603655.        6941338.
      1602655.03      6940738.02
#Sta/Elev= 30
  3663.2 1604.89  3738.7 1601.08  3766.6 1597.84    3789 1598.03  3819.7  1601.7
  3864.4 1595.36  3917.6 1596.58  3931.5 1594.81  4199.9 1584.53  4693.1 1577.01
  4693.6 1576.51  4707.3 1577.01  4722.5  1578.6  4782.5 1578.57  4790.6  1578.6
  4974.1 1579.42  4990.9 1577.17  5018.4 1579.49  5273.1  1581.8    5378 1580.45
  5479.1 1582.18    5516 1587.83  5537.4 1587.77  5580.2 1583.76  5638.5  1583.8
  5669.6 1586.48  5690.9 1584.72  5961.1 1592.55  6089.4 1603.35    6171  1605.8
#Mann= 5 ,-1 , 0
  3663.2     .05       0  4693.1     .05       0  4707.3     .05       0
  4782.5     .12       0  4790.6     .05       0
Bank Sta=4693.1,4707.3
XS Rating Curve= 0 ,0
Exp/Cntr=0.3,0.1

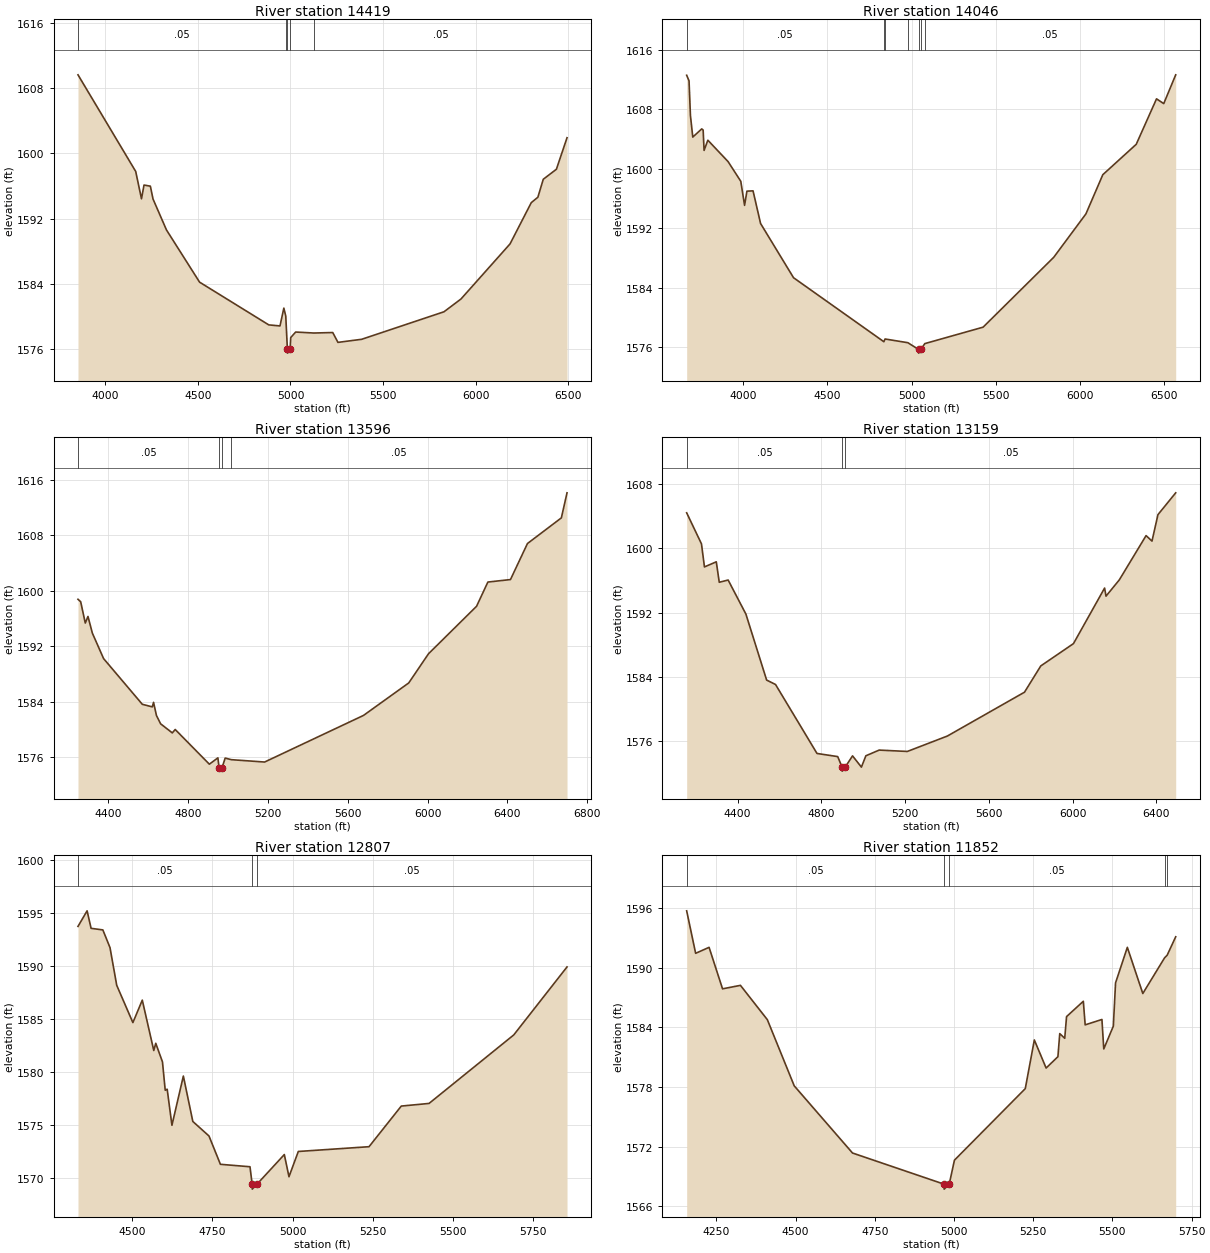
Type RM Length L Ch R = 1 ,14419   ,373,373,373
BEGIN DESCRIPTION:
Deadman 02 22.0
END DESCRIPTION:
XS GIS Cut Line= 3
      1604355.01      6942588.04       1604047.1      6941481.56
      1603155.02      6940288.03
#Sta/Elev= 30
  3853.5 1609.66  4164.9 1597.79  4196.1 1594.43  4209.8 1596.12    4244 1595.98
  4258.4  1594.4    4331  1590.6  4509.5 1584.19  4882.8 1578.94  4943.4 1578.81
  4964.2    1581  4974.6 1580.02  4978.1 1578.39  4983.3 1575.97  4983.8 1575.47
    4998 1575.97  5001.3 1577.38  5027.9 1578.06  5126.9 1577.94    5228    1578
  5256.2 1576.79  5384.3 1577.17  5828.3 1580.55    5920 1582.12  6184.7 1588.89
  6299.3 1593.96  6334.8 1594.62    6364 1596.83  6434.8 1598.06  6492.1 1601.93
#Mann= 5 ,-1 , 0
  3853.5     .05       0  4978.1     .12       0  4983.3     .07       0
    4998     .12       0  5126.9     .05       0
Bank Sta=4983.3,4998
XS Rating Curve= 0 ,0
Exp/Cntr=0.3,0.1

Type RM Length L Ch R = 1 ,14046   ,450,450,450
BEGIN DESCRIPTION:
Deadman 02 21.0
END DESCRIPTION:
XS GIS Cut Line= 3
      1605254.99        6941788.        1604055.        6941188.
      1603054.99      6939987.98
#Sta/Elev= 30
  3664.9 1612.57  3678.9 1611.82  3687.2 1607.16  3701.2 1604.26  3754.3 1605.36
  3762.7  1605.2  3768.3 1602.47  3790.7 1603.84  3910.9 1600.96  3986.3 1598.31
  4008.7 1595.08  4022.7 1596.99    4059 1597.03  4103.7 1592.64  4299.4 1585.35
  4835.9 1576.74  4842.9 1577.11  4978.5 1576.61  5041.4 1575.71  5041.9 1575.21
  5056.2 1575.71  5078.9 1576.49    5425  1578.7  5844.2 1588.09  6035.5 1593.93
  6135.8  1599.2  6334.3 1603.29  6454.7  1609.4  6497.6 1608.76  6568.6 1612.63
#Mann= 7 ,-1 , 0
  3664.9     .05       0  4835.9     .12       0  4842.9     .05       0
  4978.5     .12       0  5041.4     .07       0  5056.2     .12       0
  5078.9     .05       0
Bank Sta=5041.4,5056.2
XS Rating Curve= 0 ,0
Exp/Cntr=0.3,0.1

Type RM Length L Ch R = 1 ,13596   ,437,437,437
BEGIN DESCRIPTION:
Deadman 02 20.0
END DESCRIPTION:
XS GIS Cut Line= 3
        1605055.        6941488.        1604455.        6941038.
      1603254.97      6939837.97
#Sta/Elev= 30
  4250.9 1598.78  4264.4 1598.42  4287.4 1595.35  4300.9  1596.3  4322.8  1593.9
    4379 1590.23  4572.8 1583.64  4622.8 1583.27    4629 1583.92  4643.6 1582.02
  4664.4 1580.83  4722.8 1579.52  4737.4 1580.01  4908.2 1575.01  4950.9 1575.92
    4957 1574.51  4957.5 1574.01  4971.8 1574.51  4987.4 1575.89  5018.3 1575.66
  5184.7 1575.32  5679.7 1582.04    5906 1586.72    6005 1590.93  6245.4 1597.77
    6302 1601.26  6415.1 1601.62    6500 1606.81  6669.7 1610.51    6698 1614.12
#Mann= 4 ,-1 , 0
  4250.9     .05       0    4957     .07       0  4971.8     .05       0
  5018.3     .05       0
Bank Sta=4957,4971.8
XS Rating Curve= 0 ,0
Exp/Cntr=0.3,0.1

Type RM Length L Ch R = 1 ,13159   ,352,352,352
BEGIN DESCRIPTION:
Deadman 02 19.0
END DESCRIPTION:
XS GIS Cut Line= 3
        1605355.        6941388.        1604755.        6940788.
      1603655.02      6939788.02
#Sta/Elev= 30
  4156.9 1604.43  4227.6 1600.56  4241.8 1597.69  4298.3 1598.33  4312.5 1595.78
  4354.9 1596.06  4439.7 1591.82  4538.7  1583.6  4581.2 1583.05  4779.2 1574.46
  4878.1 1574.07  4898.9 1572.76  4899.4 1572.26  4913.9 1572.76  4948.9 1574.16
  4991.3 1572.76  5012.5 1574.17    5076 1574.88  5210.5 1574.71  5401.7 1576.63
    5770 1582.09  5847.7 1585.36  6003.8 1588.14  6152.5 1595.06  6159.2 1594.05
  6222.8 1596.08  6350.5 1601.59  6378.8 1600.91  6407.2  1604.2    6492 1606.92
#Mann= 3 ,-1 , 0
  4156.9     .05       0  4898.9     .05       0  4913.9     .05       0
Bank Sta=4898.9,4913.9
XS Rating Curve= 0 ,0
Exp/Cntr=0.3,0.1

Type RM Length L Ch R = 1 ,12807   ,955,955,955
BEGIN DESCRIPTION:
Mapping XS 54ca3eeb
END DESCRIPTION:
XS GIS Cut Line= 3
      1605400.28      6941131.09       1605033.5       6940617.6
      1604492.48      6939906.93
#Sta/Elev= 30
  4331.2 1593.72  4359.6 1595.19    4372 1593.54  4408.7 1593.39    4431 1591.72
  4451.9 1588.17  4502.3 1584.65  4531.6 1586.77  4567.4 1582.02  4573.6  1582.7
  4594.5 1580.95  4603.1 1578.27  4609.2 1578.37    4624 1574.97  4659.6 1579.61
  4689.1 1575.33  4739.5 1573.96  4775.1 1571.29  4867.3 1571.06  4873.9 1569.45
  4874.4 1568.95  4890.2 1569.45  4974.3 1572.21  4988.8 1570.12  5017.9  1572.5
  5238.3 1572.95  5338.8 1576.78  5425.4 1577.03  5689.4 1583.49  5855.4  1589.9
#Mann= 3 ,-1 , 0
  4331.2     .05       0  4873.9     .05       0  4890.2     .05       0
Bank Sta=4873.9,4890.2
XS Rating Curve= 0 ,0
Exp/Cntr=0.3,0.1

Type RM Length L Ch R = 1 ,11852   ,434,434,434
BEGIN DESCRIPTION:
Deadman 02 16.0
END DESCRIPTION:
XS GIS Cut Line= 3
      1605855.02      6940838.02        1605255.        6940238.
      1604904.99      6939637.98
#Sta/Elev= 30
  4156.5  1595.7  4184.8 1591.43  4227.2 1592.03  4269.7 1587.86  4326.2 1588.21
  4411.1 1584.76  4495.9 1578.11  4679.8 1571.36  4968.6 1568.23  4969.1 1567.73
    4985 1568.23  5001.5 1570.64    5225 1577.83  5253.6 1582.72  5290.8  1579.9
    5328 1581.04  5333.8 1583.36  5349.5 1582.89  5355.3 1585.07  5408.2 1586.61
    5414 1584.24  5466.9 1584.78  5472.7 1581.82  5502.9 1584.11  5509.9 1588.46
  5547.1 1592.03  5595.9 1587.39  5664.5 1590.97  5672.9 1591.25  5699.7 1593.09
#Mann= 5 ,-1 , 0
  4156.5     .05       0  4968.6     .05       0    4985     .05       0
  5664.5     .12       0  5672.9     .05       0
Bank Sta=4968.6,4985
XS Rating Curve= 0 ,0
Exp/Cntr=0.3,0.1

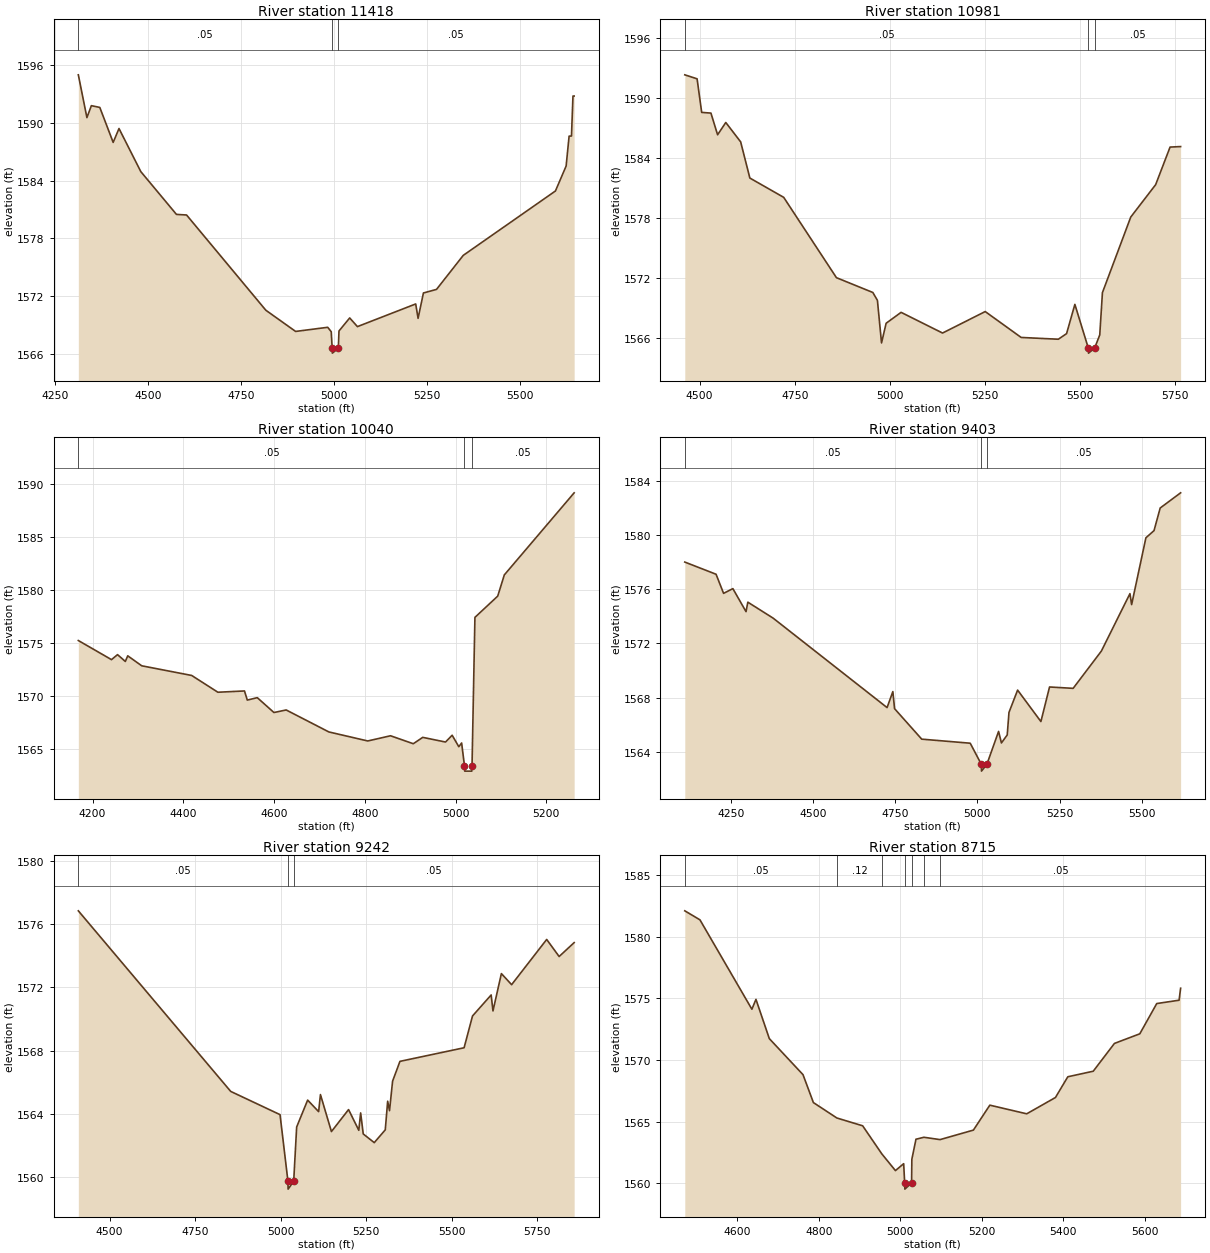
Type RM Length L Ch R = 1 ,11418   ,437,437,437
BEGIN DESCRIPTION:
Deadman 02 15.0
END DESCRIPTION:
XS GIS Cut Line= 3
      1605904.98      6940787.96        1605555.        6940188.
      1605054.99      6939787.99
#Sta/Elev= 30
  4311.9 1594.97    4335 1590.53    4347 1591.77  4369.7 1591.59  4405.7 1587.96
  4421.4  1589.4  4480.1 1584.93  4576.1 1580.49  4603.3 1580.43  4816.7 1570.55
  4896.9 1568.35  4983.3 1568.78  4992.8 1568.32  4995.3  1566.6  4995.8  1566.1
  5011.8  1566.6  5013.7  1568.4  5042.5 1569.75  5063.3 1568.85  5220.2  1571.2
  5226.6 1569.71    5241 1572.34  5276.2 1572.71  5348.2 1576.24  5596.4 1582.92
  5625.2 1585.51  5633.2 1588.61  5639.6 1588.62  5643.6 1592.77  5646.8 1592.77
#Mann= 3 ,-1 , 0
  4311.9     .05       0  4995.3     .03       0  5011.8     .05       0
Bank Sta=4995.3,5011.8
XS Rating Curve= 0 ,0
Exp/Cntr=0.3,0.1

Type RM Length L Ch R = 1 ,10981   ,941,941,941
BEGIN DESCRIPTION:
Deadman 02 14.0
END DESCRIPTION:
XS GIS Cut Line= 3
      1606105.01      6940638.02        1605905.        6940138.
      1605537.14      6939467.86
#Sta/Elev= 30
  4461.1 1592.33  4493.4 1591.93  4505.5 1588.57  4529.8  1588.5  4547.3 1586.33
  4568.8 1587.56  4607.9 1585.62  4632.1    1582    4721 1580.07  4859.6 1572.03
  4955.2 1570.55  4967.3 1569.76  4978.1  1565.5  4990.2 1567.47  5029.5 1568.56
  5138.5 1566.49  5250.6 1568.64    5345 1566.05  5442.6 1565.87  5464.4 1566.43
  5486.2 1569.36  5521.6 1564.98  5522.1 1564.48  5538.1 1564.98  5551.6  1566.3
  5558.6 1570.53  5633.1  1578.1  5698.5 1581.34  5736.4  1585.1  5764.1 1585.15
#Mann= 3 ,-1 , 0
  4461.1     .05       0  5521.6     .03       0  5538.1     .05       0
Bank Sta=5521.6,5538.1
XS Rating Curve= 0 ,0
Exp/Cntr=0.3,0.1

Type RM Length L Ch R = 1 ,10040   ,637,637,637
BEGIN DESCRIPTION:
Mapping XS 000fb6e0
END DESCRIPTION:
XS GIS Cut Line= 3
      1606093.79      6940209.09      1606180.28      6939974.33
      1605681.99      6939294.84
#Sta/Elev= 30
  4168.7 1575.26  4241.8 1573.46  4255.1 1573.93  4272.3 1573.29  4277.6 1573.82
  4308.4 1572.88  4418.5 1571.97  4476.3 1570.39  4534.9 1570.51  4541.1 1569.65
  4563.1 1569.88  4599.8 1568.48  4626.8 1568.72  4720.9 1566.65  4806.6  1565.8
  4856.8 1566.29    4907 1565.54  4927.8 1566.14    4978  1565.7  4992.6 1566.34
  5007.3 1565.26  5013.5 1565.61  5019.8 1563.46  5020.3 1562.96  5035.9 1562.96
  5036.4 1563.46  5042.8 1577.44    5093 1579.44  5107.6 1581.44  5261.5 1589.17
#Mann= 3 ,-1 , 0
  4168.7     .05       0  5019.8     .05       0  5036.4     .05       0
Bank Sta=5019.8,5036.4
XS Rating Curve= 0 ,0
Exp/Cntr=0.3,0.1

Type RM Length L Ch R = 1 ,9403    ,161,161,161
BEGIN DESCRIPTION:
Mapping XS 24de85d5
END DESCRIPTION:
XS GIS Cut Line= 4
       1606069.7      6940319.61      1606184.34      6940076.57
      1606436.52      6939320.04      1606532.81      6938889.04
#Sta/Elev= 30
  4110.4 1578.01  4205.5 1577.11  4228.3  1575.7  4256.6 1576.05  4296.6 1574.35
  4302.1 1575.05  4379.1 1573.87  4725.5 1567.27  4743.1 1568.45  4748.3 1567.19
  4830.9 1564.94  4978.4 1564.64  5012.2 1563.08  5012.7 1562.58    5029 1563.08
  5064.6 1565.51  5073.3 1564.66  5090.9 1565.25  5096.2 1566.91  5122.5 1568.56
  5193.3 1566.24  5219.6 1568.79  5291.4 1568.69  5377.2 1571.44  5464.1 1575.68
  5469.2 1574.87  5512.6  1579.8  5537.3 1580.33  5556.1    1582  5618.2 1583.12
#Mann= 3 ,-1 , 0
  4110.4     .05       0  5012.2     .03       0    5029     .05       0
Bank Sta=5012.2,5029
XS Rating Curve= 0 ,0
Exp/Cntr=0.3,0.1

Type RM Length L Ch R = 1 ,9242    ,527,527,527
BEGIN DESCRIPTION:
Mapping XS 58a6b08f
END DESCRIPTION:
XS GIS Cut Line= 3
      1606344.82      6940099.48      1606574.07      6939384.23
      1606826.25      6938733.15
#Sta/Elev= 30
  4408.4 1576.84  4853.8 1565.42    4998 1563.95  5021.1 1559.74  5021.6 1559.24
  5037.9 1559.74  5046.6 1563.17  5078.7 1564.87  5110.8 1564.14  5116.1 1565.22
  5148.2 1562.88  5198.3 1564.27  5228.2 1562.96  5233.6 1564.06  5241.2 1562.73
  5273.4 1562.18  5305.6 1562.99  5312.6  1564.8    5318  1564.2    5327 1566.07
  5348.5 1567.32    5536 1568.18  5560.6 1570.19  5615.1 1571.52  5620.4 1570.51
    5645 1572.87  5674.9 1572.17  5777.4 1575.03  5813.8 1573.95  5857.7 1574.83
#Mann= 3 ,-1 , 0
  4408.4     .05       0  5021.1     .05       0  5037.9     .05       0
Bank Sta=5021.1,5037.9
XS Rating Curve= 0 ,0
Exp/Cntr=0.3,0.1

Type RM Length L Ch R = 1 ,8715    ,732,732,732
BEGIN DESCRIPTION:
Mapping XS 3e096db9
END DESCRIPTION:
XS GIS Cut Line= 3
      1606904.19      6939911.53      1606794.15      6938985.34
      1606871.71      6938711.61
#Sta/Elev= 30
  4471.1 1582.08  4508.3 1581.35  4635.8 1574.11  4645.8 1574.91  4678.6 1571.73
  4761.3 1568.81  4786.8 1566.55  4844.5  1565.3  4907.7 1564.67  4954.9 1562.39
  4988.2 1561.04  5008.4  1561.6  5010.9 1560.04  5011.4 1559.54  5027.8 1560.04
  5028.5 1561.96  5038.6 1563.58  5058.1 1563.74  5097.7 1563.55  5179.6 1564.32
  5219.9 1566.34  5310.5 1565.64    5381 1566.96  5411.4 1568.64  5473.8 1569.09
  5525.8 1571.34  5588.1 1572.12  5629.7 1574.57  5684.5 1574.84  5688.3 1575.81
#Mann= 7 ,-1 , 0
  4471.1     .05       0  4844.5     .12       0  4954.9     .05       0
  5010.9     .05       0  5027.8     .05       0  5058.1     .12       0
  5097.7     .05       0
Bank Sta=5010.9,5027.8
XS Rating Curve= 0 ,0
Exp/Cntr=0.3,0.1

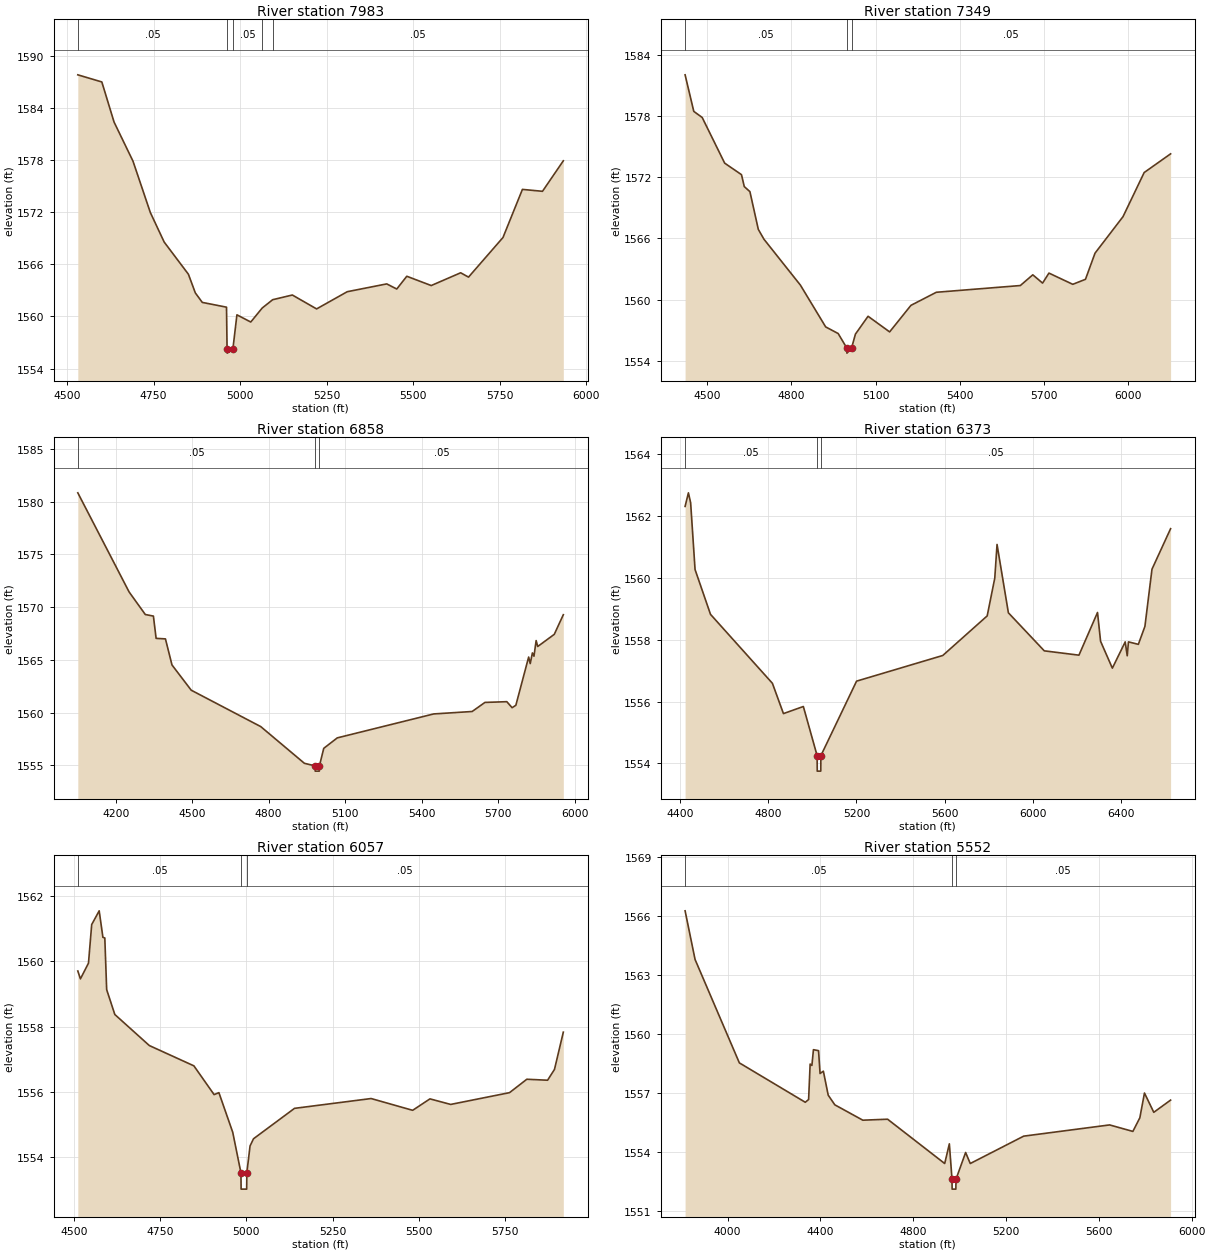
Type RM Length L Ch R = 1 ,7983    ,634,634,634
BEGIN DESCRIPTION:
Mapping XS 4a4f16a4
END DESCRIPTION:
XS GIS Cut Line= 3
      1607335.18      6939847.32       1607298.5      6939104.55
      1606895.44      6938582.39
#Sta/Elev= 30
  4531.1 1587.82  4600.5    1587  4635.9 1582.38  4690.6 1577.88  4740.7 1571.97
  4780.7 1568.57  4850.8 1564.86  4870.8 1562.71  4890.9 1561.62  4960.9 1561.07
  4962.5 1556.28    4963 1555.78  4979.4 1556.28    4991 1560.19    5031 1559.36
    5064 1560.97  5094.3 1561.93  5151.2 1562.47  5221.3 1560.87  5309.8 1562.85
    5424 1563.75    5453 1563.16    5482 1564.63  5552.6 1563.56  5637.7 1565.03
  5660.4 1564.53    5760 1569.09  5816.2 1574.63  5874.2 1574.41  5934.4 1577.92
#Mann= 5 ,-1 , 0
  4531.1     .05       0  4962.5     .05       0  4979.4     .05       0
    5064     .12       0  5094.3     .05       0
Bank Sta=4962.5,4979.4
XS Rating Curve= 0 ,0
Exp/Cntr=0.3,0.1

Type RM Length L Ch R = 1 ,7349    ,491,491,491
BEGIN DESCRIPTION:
Mapping XS 14040724
END DESCRIPTION:
XS GIS Cut Line= 3
      1607857.88      6939939.03      1607844.12       6939393.4
      1607330.61      6938325.11
#Sta/Elev= 30
  4421.1 1582.01  4452.1 1578.43  4482.1 1577.83  4562.2 1573.36  4622.2 1572.23
  4632.2 1571.06  4652.2 1570.57  4682.2 1566.87  4702.2 1565.91  4832.3 1561.41
  4922.3 1557.32  4966.9 1556.67  4997.7 1555.25  4998.2 1554.75  5014.7 1555.25
  5028.4 1556.61  5073.5 1558.36  5150.4 1556.83  5226.4 1559.43  5316.8 1560.71
  5616.4 1561.37  5660.8 1562.42  5695.8 1561.61  5718.4 1562.59  5803.4 1561.49
  5848.7 1561.98  5882.7 1564.54  5982.6 1568.12    6058 1572.44  6152.2 1574.27
#Mann= 3 ,-1 , 0
  4421.1     .05       0  4997.7     .05       0  5014.7     .05       0
Bank Sta=4997.7,5014.7
XS Rating Curve= 0 ,0
Exp/Cntr=0.3,0.1

Type RM Length L Ch R = 1 ,6858    ,485,485,485
BEGIN DESCRIPTION:
Mapping XS 9a461fae
END DESCRIPTION:
XS GIS Cut Line= 4
      1608096.29      6940007.83       1608247.6       6939576.8
      1608183.41      6939072.45      1607629.91       6938313.1
#Sta/Elev= 30
  4051.2 1580.83  4252.4 1571.44    4316  1569.3  4347.8 1569.15  4358.4 1567.04
    4395 1566.99  4420.7 1564.52  4496.1 1562.13  4768.9 1558.68  4940.3  1555.2
  4982.2 1554.96  4982.7 1554.46  4998.7 1554.46  4999.2 1554.96  5016.2 1556.62
  5069.2 1557.61  5447.8 1559.88  5598.4 1560.11  5648.6 1560.97  5734.4 1561.04
  5755.2 1560.47  5769.9  1560.7  5820.1 1565.27  5826.3 1564.65  5834.8 1565.66
    5841 1565.35  5849.5 1566.83  5855.7 1566.27  5920.6 1567.42  5956.1 1569.28
#Mann= 3 ,-1 , 0
  4051.2     .05       0  4982.2    .035       0  4999.2     .05       0
Bank Sta=4982.2,4999.2
XS Rating Curve= 0 ,0
Exp/Cntr=0.3,0.1

Type RM Length L Ch R = 1 ,6373    ,316,316,316
BEGIN DESCRIPTION:
Deadman 02 7.0
END DESCRIPTION:
XS GIS Cut Line= 3
        1608630.      6939713.03        1608655.        6939138.
      1607934.38      6937683.83
#Sta/Elev= 30
  4423.9 1562.31  4438.9 1562.75    4449 1562.43    4469 1560.27    4539 1558.82
  4819.3 1556.59  4869.3 1555.61  4959.4 1555.84  5021.8 1554.25  5022.3 1553.75
  5038.3 1553.75  5038.8 1554.25  5200.4 1556.66  5590.8 1557.49  5791.9 1558.77
  5826.2 1559.99  5836.5 1561.08  5887.9 1558.87  6050.4 1557.64  6207.4  1557.5
  6291.5 1558.88  6305.3 1557.95  6358.7 1557.08  6416.9 1557.93    6426 1557.48
  6431.6 1557.93  6476.4 1557.85  6506.1 1558.43  6538.1 1560.28  6622.4 1561.59
#Mann= 3 ,-1 , 0
  4423.9     .05       0  5021.8    .035       0  5038.8     .05       0
Bank Sta=5021.8,5038.8
XS Rating Curve= 0 ,0
Exp/Cntr=0.3,0.1

Type RM Length L Ch R = 1 ,6057    ,505,505,505
BEGIN DESCRIPTION:
Deadman 02 6.0
END DESCRIPTION:
XS GIS Cut Line= 3
      1608749.38      6939754.95      1608904.63      6939390.46
      1608970.65       6938382.5
#Sta/Elev= 30
  4511.6  1559.7  4519.2 1559.46  4542.5 1559.94  4551.8 1561.12  4573.5 1561.54
  4584.3 1560.73  4589.8 1560.71  4595.2 1559.13  4618.8 1558.37  4718.8 1557.42
  4847.8  1556.8  4906.4 1555.92  4920.3 1555.98  4960.3 1554.77  4984.1 1553.53
  4984.6 1553.03  5000.7 1553.03  5001.2 1553.53  5010.5 1554.35  5020.5 1554.57
  5139.3  1555.5  5361.2  1555.8  5481.5 1555.44  5531.6 1555.79  5591.7 1555.62
  5762.1 1555.98  5812.2 1556.39  5872.3 1556.36  5892.3 1556.69  5917.9 1557.83
#Mann= 3 ,-1 , 0
  4511.6     .05       0  4984.1    .035       0  5001.2     .05       0
Bank Sta=4984.1,5001.2
XS Rating Curve= 0 ,0
Exp/Cntr=0.3,0.1

Type RM Length L Ch R = 1 ,5552    ,278,278,278
BEGIN DESCRIPTION:
Mapping XS 95b71300
END DESCRIPTION:
XS GIS Cut Line= 4
      1608688.65      6940072.12      1609316.32      6939532.19
      1609363.56      6939370.21      1609308.69      6938275.56
#Sta/Elev= 30
  3816.5 1566.25  3859.5 1563.78  4050.4 1558.53  4334.6 1556.53  4348.9 1556.67
  4355.5 1558.47  4363.1  1558.4  4369.7  1559.2  4391.7 1559.15  4398.3 1557.99
  4412.5 1558.11  4433.4 1556.89  4461.9  1556.4  4582.6 1555.62  4689.3 1555.67
  4935.5 1553.42  4955.6 1554.42    4967 1552.62  4967.5 1552.12  4983.6 1552.12
  4984.1 1552.62  5025.7 1553.98  5045.7 1553.42    5276 1554.81  5646.4 1555.38
  5746.6 1555.05  5776.6 1555.74  5796.6    1557  5836.7 1556.02  5909.2 1556.64
#Mann= 3 ,-1 , 0
  3816.5     .05       0    4967     .03       0  4984.1     .05       0
Bank Sta=4967,4984.1
XS Rating Curve= 0 ,0
Exp/Cntr=0.3,0.1

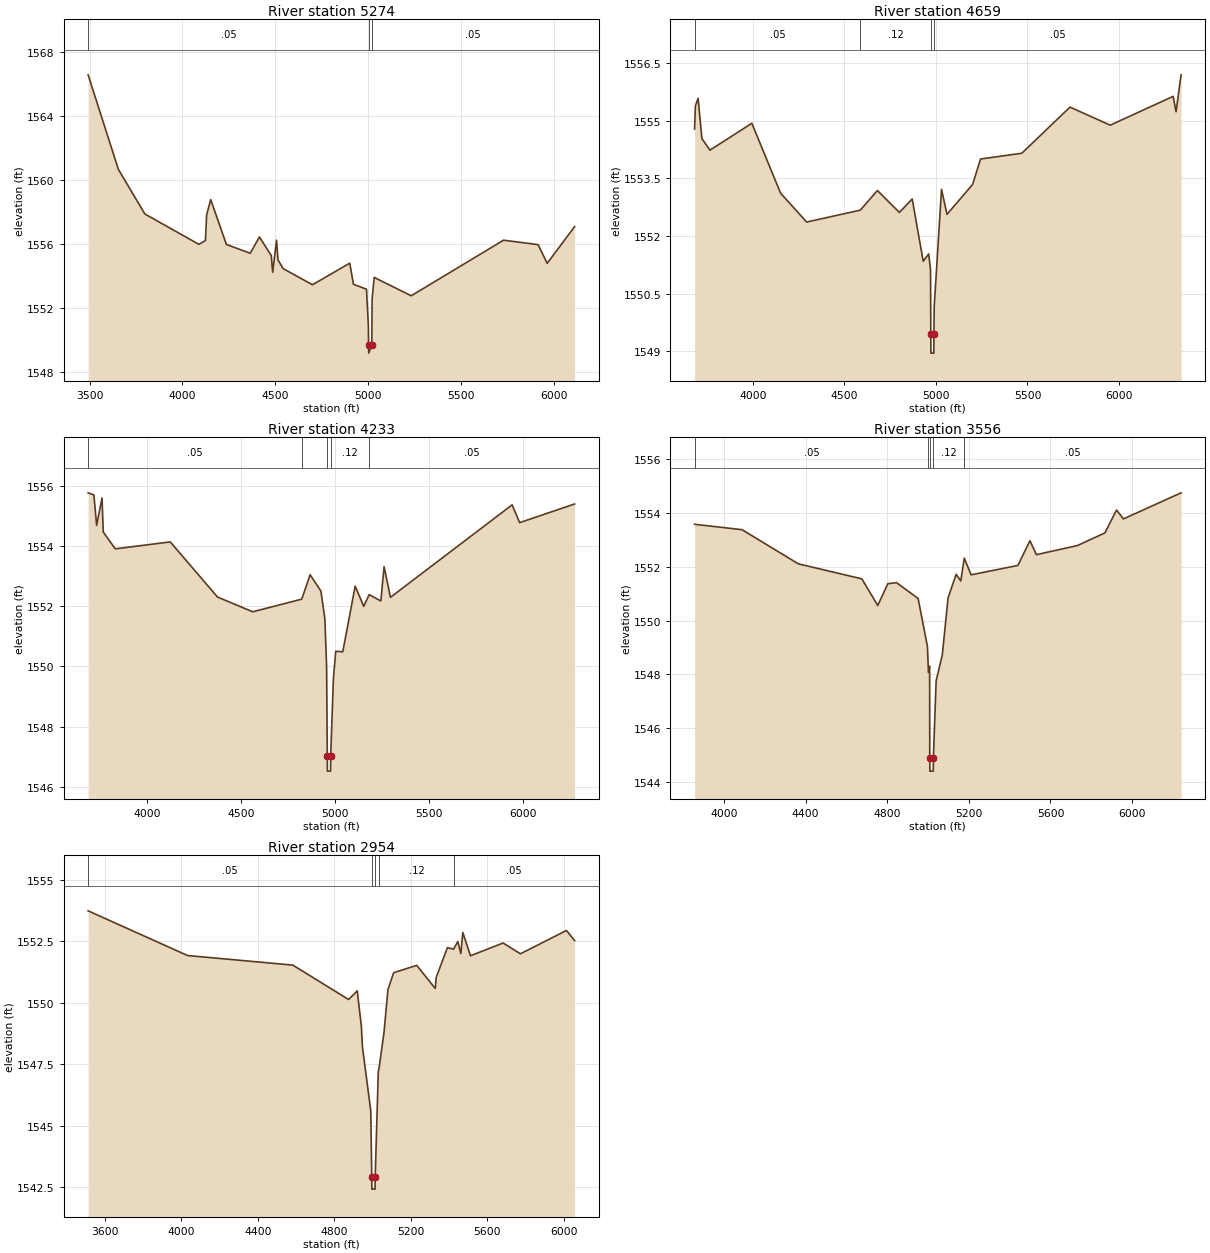
Type RM Length L Ch R = 1 ,5274    ,615,615,615
BEGIN DESCRIPTION:
Deadman 02 5.0
END DESCRIPTION:
XS GIS Cut Line= 4
      1608704.98      6940138.02      1609599.78      6939356.71
      1609536.95      6938257.29      1609417.25      6937952.68
#Sta/Elev= 30
  3492.5  1566.6  3655.3 1560.68  3797.7 1557.89  4088.2 1555.99  4123.3 1556.22
  4129.9 1557.83  4151.8 1558.79  4236.3 1555.98  4364.4 1555.43  4413.8 1556.45
  4477.4 1555.29    4485 1554.24  4505.9 1556.25  4513.5 1555.02  4541.3 1554.47
  4699.1 1553.46  4899.5 1554.81  4919.5 1553.49  4989.6 1553.18  4999.6 1550.93
    5001 1549.68  5001.5 1549.18  5018.2 1549.68  5019.7 1552.54  5030.9 1553.92
    5230 1552.77    5727 1556.25  5912.6 1555.97  5961.4  1554.8  6108.9  1557.1
#Mann= 3 ,-1 , 0
  3492.5     .05       0    5001     .05       0  5018.2     .05       0
Bank Sta=5001,5018.2
XS Rating Curve= 0 ,0
Exp/Cntr=0.3,0.1

Type RM Length L Ch R = 1 ,4659    ,426,426,426
BEGIN DESCRIPTION:
Mapping XS c2bc7be6
END DESCRIPTION:
XS GIS Cut Line= 4
      1609467.22      6939806.31      1609999.53      6939061.75
      1609975.94      6938441.87       1609416.7      6937468.25
#Sta/Elev= 30
  3681.2 1554.78  3685.6 1555.38  3700.4 1555.58  3721.3 1554.53  3765.2 1554.23
    3994 1554.93  4151.3 1553.11  4293.8 1552.36  4586.8 1552.67  4680.3 1553.18
  4800.4 1552.61  4870.4 1552.96  4930.5 1551.34  4960.5 1551.53  4970.5 1551.12
  4971.9 1549.45  4972.4 1548.95  4988.6 1548.95  4989.1 1549.45  4990.5 1550.15
  5030.5 1553.21  5060.6 1552.56  5200.7 1553.34  5243.7    1554  5469.4 1554.15
  5732.6 1555.35  5952.5 1554.88  6296.2 1555.63    6312 1555.23  6339.6 1556.19
#Mann= 4 ,-1 , 0
  3681.2     .05       0  4586.8     .12       0  4971.9     .05       0
  4989.1     .05       0
Bank Sta=4971.9,4989.1
XS Rating Curve= 0 ,0
Exp/Cntr=0.3,0.1

Type RM Length L Ch R = 1 ,4233    ,677,677,677
BEGIN DESCRIPTION:
Mapping XS 3b4e42a5
END DESCRIPTION:
XS GIS Cut Line= 5
      1609440.22      6939996.55      1609765.07      6939600.14
      1610221.87      6938900.04      1610349.89      6938630.53
      1610265.67      6937697.35
#Sta/Elev= 30
  3688.6 1555.76  3719.4 1555.69  3733.8 1554.68  3762.5 1555.59    3769 1554.46
  3832.8  1553.9  4124.9 1554.13  4375.8  1552.3  4562.8 1551.81  4823.3 1552.23
  4867.6 1553.04  4924.9  1552.5    4946 1551.58  4955.2 1549.99  4958.9 1547.02
  4959.4 1546.52  4976.3 1546.52  4976.8 1547.02  4991.4  1549.6  5003.7  1550.5
    5041 1550.48  5106.9 1552.66  5152.4 1551.99  5181.1 1552.38  5243.3 1552.17
  5260.5 1553.31  5294.3 1552.29  5940.4 1555.36  5980.6 1554.77  6272.4 1555.39
#Mann= 5 ,-1 , 0
  3688.6     .05       0  4823.3     .12       0  4958.9     .07       0
  4976.8     .12       0  5181.1     .05       0
Bank Sta=4958.9,4976.8
XS Rating Curve= 0 ,0
Exp/Cntr=0.3,0.1

Type RM Length L Ch R = 1 ,3556    ,602,602,602
BEGIN DESCRIPTION:
Mapping XS 3400aed2
END DESCRIPTION:
XS GIS Cut Line= 4
      1609730.02      6939971.34      1610555.39      6939189.77
      1610659.83      6938974.16      1610548.65      6937973.59
#Sta/Elev= 30
  3856.7 1553.58  4088.9 1553.38  4364.8 1552.11  4676.1 1551.55  4753.9 1550.56
  4803.3 1551.37  4845.8 1551.41  4951.7 1550.82  4997.2 1549.04  5002.4 1548.07
    5008  1548.3  5008.6  1544.9  5009.1  1544.4    5026  1544.4  5026.5  1544.9
  5039.8 1547.75  5070.2 1548.73  5098.3 1550.84  5137.9 1551.72  5160.5 1551.47
  5177.6 1552.32  5211.2  1551.7  5440.4 1552.05  5499.4 1552.97    5531 1552.45
  5732.2 1552.79  5866.7 1553.26  5923.4 1554.11  5957.2 1553.78  6239.7 1554.75
#Mann= 5 ,-1 , 0
  3856.7     .05       0  5002.4     .12       0  5008.6     .05       0
  5026.5     .12       0  5177.6     .05       0
Bank Sta=5008.6,5026.5
XS Rating Curve= 0 ,0
Exp/Cntr=0.3,0.1

Type RM Length L Ch R = 1 ,2954    ,0,0,0
BEGIN DESCRIPTION:
Deadman 02 4.0
END DESCRIPTION:
XS GIS Cut Line= 3
      1609708.51      6940223.25       1610998.1      6939472.08
      1610906.92      6938425.66
#Sta/Elev= 30
  3513.4 1553.74  4033.2 1551.92  4583.3 1551.53  4874.9 1550.13    4920 1550.48
  4941.5 1549.05  4947.3 1548.19  4990.7  1545.6  4995.8 1542.91  4996.3 1542.41
  5013.4 1542.41  5013.9 1542.91    5030 1547.17  5035.3  1547.4  5060.1  1548.8
  5080.2 1550.52  5110.3 1551.22  5230.7 1551.52  5327.8 1550.58  5332.8 1551.03
  5391.3 1552.24  5423.6 1552.18  5445.6 1552.49  5461.6    1552  5471.7 1552.86
  5511.8 1551.91  5682.4 1552.43  5772.8 1551.99  6013.7 1552.94  6056.2 1552.53
#Mann= 5 ,-1 , 0
  3513.4     .05       0  4995.8     .05       0  5013.9     .05       0
  5035.3     .12       0  5423.6     .05       0
Bank Sta=4995.8,5013.9
XS Rating Curve= 0 ,0
Exp/Cntr=0.3,0.1

Chan Stop Cuts=-1
Use User Specified Reach Order=0
Composite Channel Slope=5