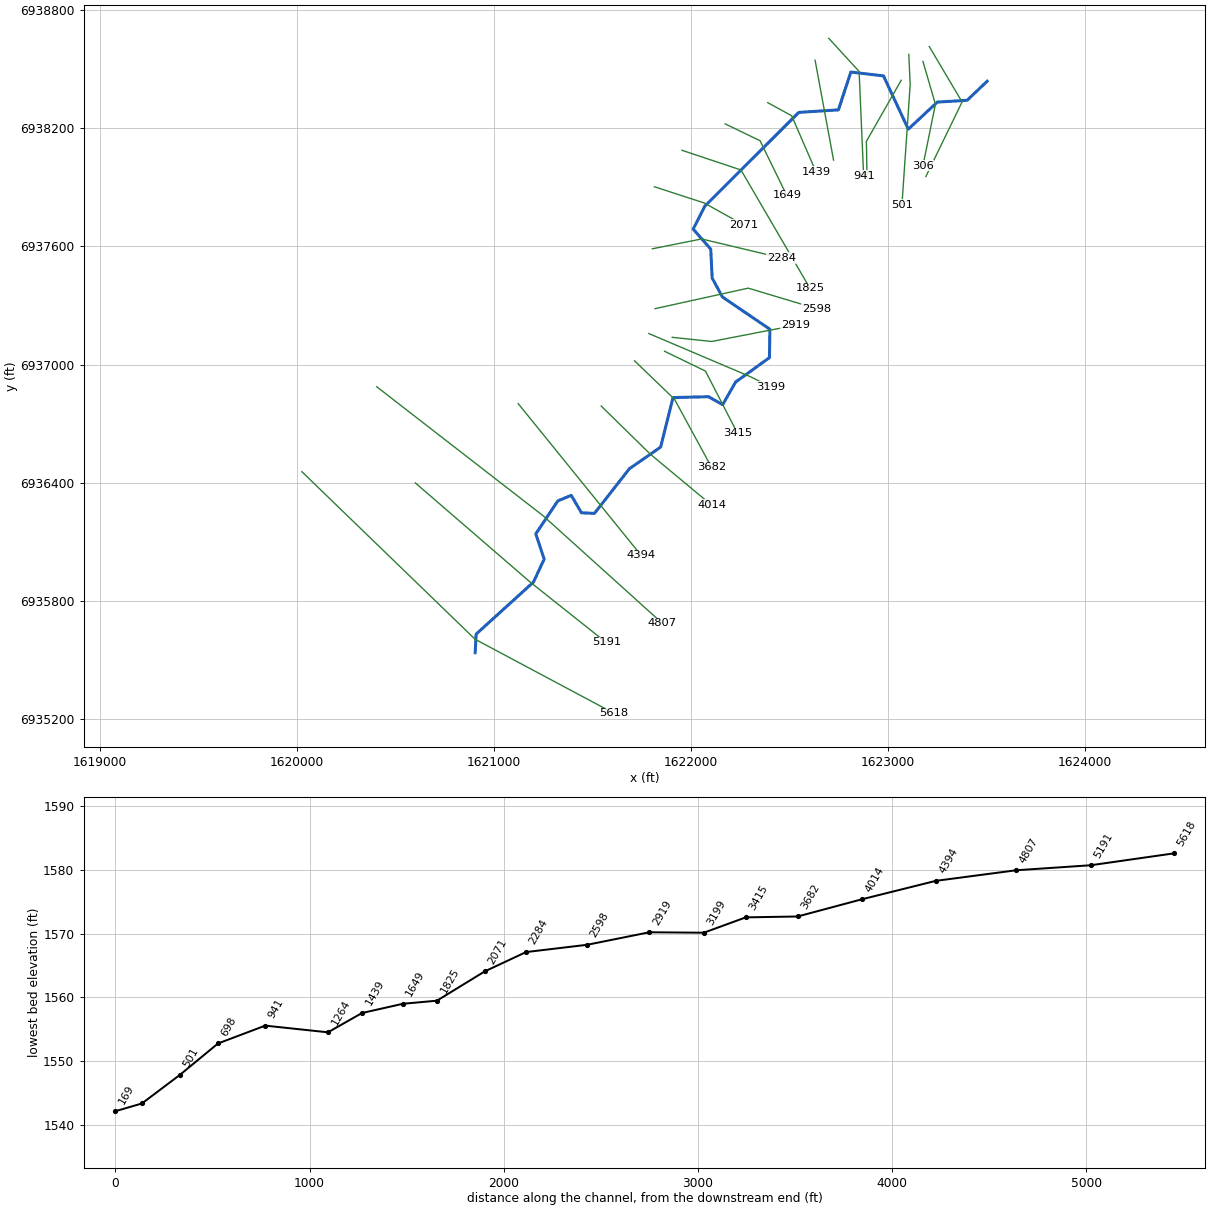
--- Deadman 03.prj (project) ---

Proj Title=Deadman 03 Base Level Engineering
Current Plan=p01
Default Exp/Contr=0.3,0.1
English Units
Geom File=g01
Flow File=f01
Plan File=p01
BEGIN DESCRIPTION:
Deadman 03
END DESCRIPTION:

--- Deadman 03.p01 (plan) ---

Plan Title=Multiple Run
Short Identifier=Multiple
Geom File=g01
Flow File=f01
Subcritical Flow
K Sum by GR= 0
Std Step Tol= 0.01
Critical Tol= 0.01
Num of Std Step Trials= 20
Max Error Tol= 0.3
Flow Tol Ratio= 0.001
Split Flow NTrial= 30
Split Flow Tol= 0.02
Split Flow Ratio= 0.02
Log Output Level= 0
Friction Slope Method= 1
Unsteady Friction Slope Method= 2
Unsteady Bridges Friction Slope Method= 1
Parabolic Critical Depth
Global Vel Dist=  1 , 1 , 1
Global Log Level= 0
CheckData=True
Encroach Param= -1, 0, 0, 0
BEGIN DESCRIPTION:
Multiple Run
END DESCRIPTION:

--- Deadman 03.f01 (steady flow) ---

Flow Title=Multiple
Number of Profiles=7
Profile Names=10-year,25-year,50-year,1pct_min,100-year,1pct_plu,500-year
River Rch & RM= Deadman 03,Reach-1,5618
     290     403     496     305     608    1213     922
Boundary for River Rch & Prof#=Deadman 03,Reach-1,1
Up Type=0
Dn Type=3
Dn Slope=0.005
Boundary for River Rch & Prof#=Deadman 03,Reach-1,2
Up Type=0
Dn Type=3
Dn Slope=0.005
Boundary for River Rch & Prof#=Deadman 03,Reach-1,3
Up Type=0
Dn Type=3
Dn Slope=0.005
Boundary for River Rch & Prof#=Deadman 03,Reach-1,4
Up Type=0
Dn Type=3
Dn Slope=0.005
Boundary for River Rch & Prof#=Deadman 03,Reach-1,5
Up Type=0
Dn Type=3
Dn Slope=0.005
Boundary for River Rch & Prof#=Deadman 03,Reach-1,6
Up Type=0
Dn Type=3
Dn Slope=0.005
Boundary for River Rch & Prof#=Deadman 03,Reach-1,7
Up Type=0
Dn Type=3
Dn Slope=0.005

--- Deadman 03.g01 (geometry) ---

Geom Title=Existing Conditions

River Reach=Deadman 03,Reach-1
Reach XY= 30
      1620905.00      6935538.00      1620910.00      6935632.69
      1621201.16      6935896.62      1621255.41      6936012.99
      1621213.04      6936141.32      1621324.86      6936308.67
      1621392.96      6936336.85      1621445.03      6936248.11
      1621511.03      6936245.45      1621687.92      6936471.58
      1621846.98      6936581.66      1621910.01      6936833.00
      1622089.85      6936837.34      1622162.02      6936797.01
      1622227.86      6936911.82      1622399.55      6937035.54
      1622401.94      6937179.69      1622160.59      6937343.61
      1622108.75      6937439.53      1622101.43      6937586.53
      1622012.30      6937687.92      1622071.63      6937804.67
      1622548.81      6938280.19      1622749.92      6938293.03
      1622813.28      6938484.95      1622978.90      6938465.30
      1623104.76      6938194.97      1623252.55      6938332.53
      1623403.55      6938341.49      1623505.00      6938438.00

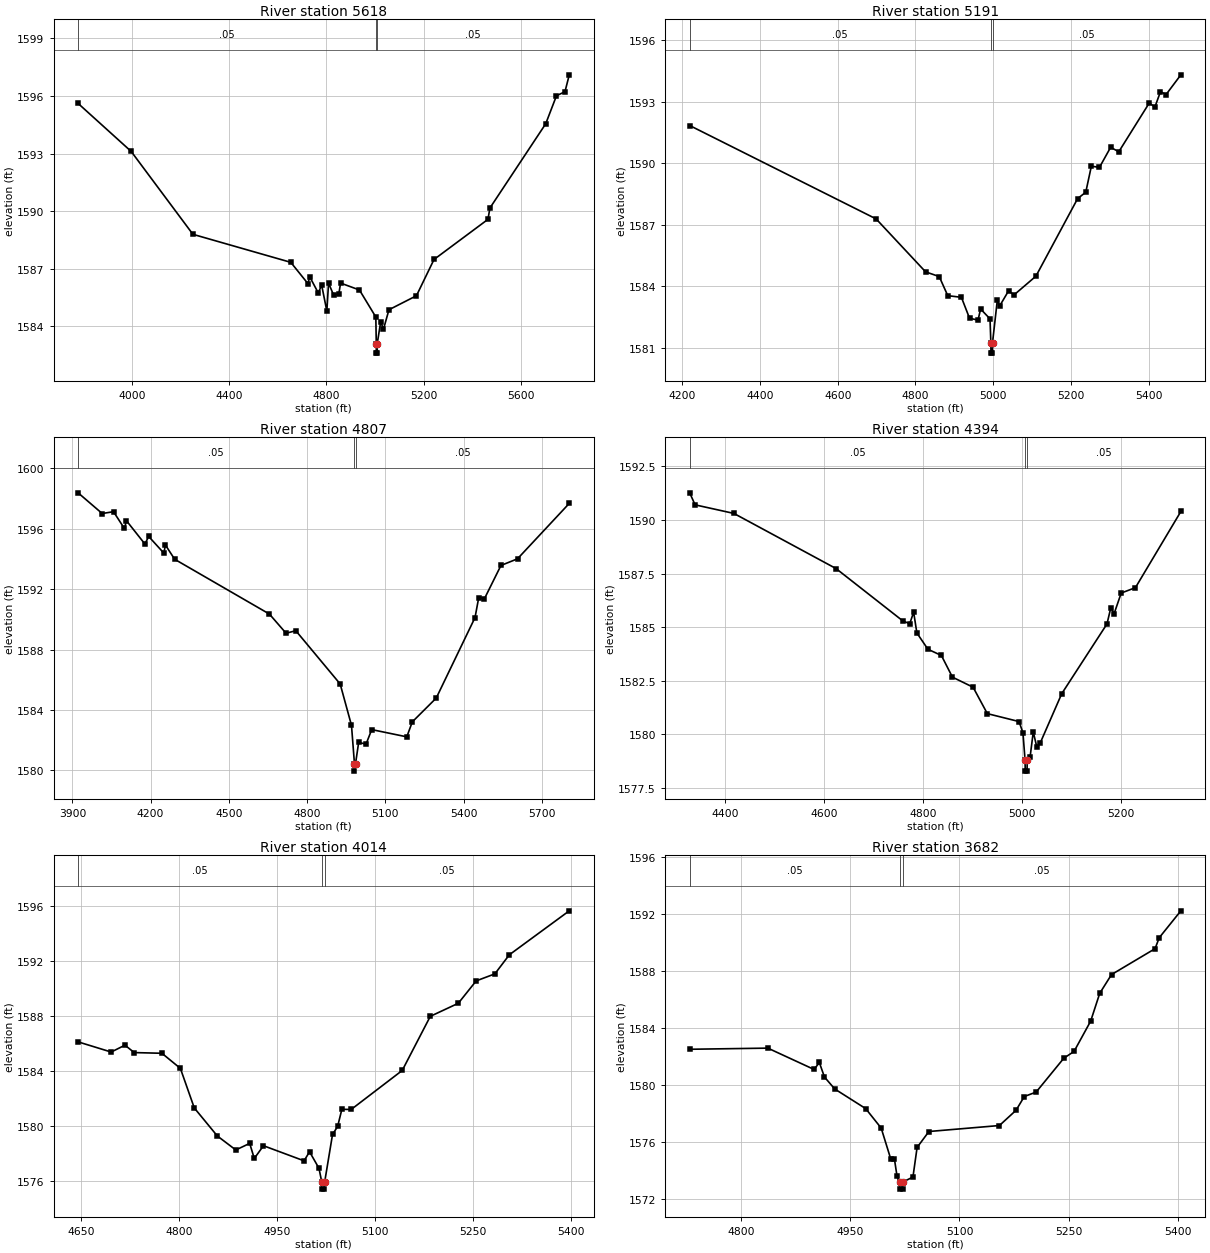
Type RM Length L Ch R = 1,5618,427,427,427
BEGIN DESCRIPTION:
Deadman 03 11.0
END DESCRIPTION:
XS GIS Cut Line= 3
      1620024.88      6936456.94      1620904.66      6935606.61
      1621610.63      6935230.40
#Sta/Elev= 30
  3776.9 1595.61  3995.5 1593.11  4249.9 1588.79  4653.2 1587.33  4723.8 1586.22
  4731.0 1586.58  4766.2 1585.74  4780.4 1586.14  4801.7 1584.79  4808.7 1586.25
  4830.0 1585.61  4851.1 1585.69  4858.3 1586.25  4936.0 1585.89  5003.5 1584.48
  5005.3 1583.10  5005.5 1582.60  5009.1 1582.60  5009.4 1583.10  5023.5 1584.24
  5034.9 1583.84  5057.5 1584.86  5170.8 1585.59  5243.2 1587.48  5465.4 1589.57
  5473.5 1590.16  5703.4 1594.55  5747.7 1596.01  5782.7 1596.22  5800.4 1597.10
#Mann=3,-1,0
  3776.9    0.05       0  5005.3    0.05       0  5009.4    0.05       0
Bank Sta=5005.3,5009.4
Exp/Cntr=0.3,0.1

Type RM Length L Ch R = 1,5191,384,384,384
BEGIN DESCRIPTION:
Mapping XS 681ff3ec
END DESCRIPTION:
XS GIS Cut Line= 3
      1620601.20      6936399.89      1621183.26      6935897.72
      1621570.63      6935590.10
#Sta/Elev= 30
  4219.3 1591.83  4698.8 1587.28  4826.1 1584.70  4861.2 1584.47  4883.1 1583.54
  4918.2 1583.46  4939.1 1582.44  4961.0 1582.35  4967.6 1582.89  4991.8 1582.41
  4994.0 1581.24  4994.3 1580.74  4997.9 1580.74  4998.2 1581.24  5010.6 1583.32
  5017.0 1583.05  5039.4 1583.77  5053.8 1583.58  5109.9 1584.49  5217.2 1588.27
  5238.1 1588.58  5252.5 1589.85  5273.3 1589.79  5302.1 1590.77  5323.0 1590.55
  5401.5 1592.93  5415.9 1592.73  5430.3 1593.48  5444.7 1593.34  5482.7 1594.30
#Mann=3,-1,0
  4219.3    0.05       0  4994.0    0.05       0  4998.2    0.05       0
Bank Sta=4994,4998.2
Exp/Cntr=0.3,0.1

Type RM Length L Ch R = 1,4807,413,413,413
BEGIN DESCRIPTION:
Deadman 03 10.0
END DESCRIPTION:
XS GIS Cut Line= 3
      1620404.97      6936888.02      1621248.74      6936234.43
      1621855.02      6935687.98
#Sta/Elev= 30
  3922.0 1598.38  4014.4 1597.01  4057.8 1597.13  4099.5 1596.02  4107.6 1596.53
  4178.2 1594.99  4192.7 1595.49  4250.7 1594.39  4257.0 1594.92  4292.3 1593.98
  4655.7 1590.35  4719.6 1589.08  4756.8 1589.25  4927.0 1585.72  4970.4 1582.98
  4981.7 1580.45  4981.9 1579.95  4985.9 1580.45  4997.9 1581.85  5026.3 1581.74
  5048.0 1582.70  5182.5 1582.22  5203.5 1583.21  5295.4 1584.79  5444.1 1590.12
  5458.3 1591.44  5480.0 1591.36  5543.5 1593.57  5607.0 1594.01  5805.5 1597.68
#Mann=3,-1,0
  3922.0    0.05       0  4981.7    0.03       0  4985.9    0.05       0
Bank Sta=4981.7,4985.9
Exp/Cntr=0.3,0.1

Type RM Length L Ch R = 1,4394,380,380,380
BEGIN DESCRIPTION:
Mapping XS 269ec2f9
END DESCRIPTION:
XS GIS Cut Line= 2
      1621123.73      6936802.15      1621748.05      6936032.15
#Sta/Elev= 30
  4328.8 1591.26  4339.7 1590.70  4418.0 1590.30  4624.2 1587.73  4759.0 1585.29
  4772.9 1585.16  4780.8 1585.70  4787.3 1584.73  4809.6 1583.97  4836.8 1583.68
  4859.1 1582.67  4900.8 1582.20  4929.5 1580.97  4993.5 1580.60  5001.4 1580.08
  5005.7 1578.79  5006.0 1578.29  5009.7 1578.29  5010.0 1578.79  5015.8 1578.94
  5022.2 1580.12  5029.3 1579.42  5036.6 1579.62  5079.7 1581.90  5171.0 1585.15
  5178.8 1585.91  5185.3 1585.62  5199.7 1586.59  5228.4 1586.84  5320.1 1590.39
#Mann=3,-1,0
  4328.8    0.05       0  5005.7    0.05       0  5010.0    0.05       0
Bank Sta=5005.7,5010
Exp/Cntr=0.3,0.1

Type RM Length L Ch R = 1,4014,332,332,332
BEGIN DESCRIPTION:
Deadman 03 9.0
END DESCRIPTION:
XS GIS Cut Line= 3
      1621545.26      6936789.93      1621795.22      6936545.17
      1622105.03      6936287.97
#Sta/Elev= 30
  4645.5 1586.12  4696.2 1585.38  4717.3 1585.88  4731.5 1585.34  4773.9 1585.29
  4802.2 1584.19  4823.5 1581.31  4858.8 1579.27  4887.1 1578.25  4908.4 1578.73
  4915.4 1577.63  4929.5 1578.56  4991.7 1577.46  5000.1 1578.12  5014.5 1576.92
  5018.9 1575.90  5019.1 1575.40  5022.9 1575.40  5023.2 1575.90  5035.3 1579.38
  5043.1 1579.96  5049.6 1581.21  5063.9 1581.20  5142.1 1584.04  5185.1 1587.98
  5228.0 1588.93  5255.4 1590.56  5284.0 1591.07  5306.2 1592.46  5398.0 1595.66
#Mann=3,-1,0
  4645.5    0.05       0  5018.9    0.03       0  5023.2    0.05       0
Bank Sta=5018.9,5023.2
Exp/Cntr=0.3,0.1

Type RM Length L Ch R = 1,3682,267,267,267
BEGIN DESCRIPTION:
Deadman 03 8.0
END DESCRIPTION:
XS GIS Cut Line= 3
      1621714.67      6937019.27      1621917.37      6936824.68
      1622105.49      6936479.27
#Sta/Elev= 30
  4729.6 1582.52  4836.9 1582.60  4900.4 1581.10  4907.6 1581.59  4914.6 1580.57
  4928.7 1579.73  4971.2 1578.35  4992.5 1576.98  5005.5 1574.83  5010.6 1574.83
  5014.3 1573.58  5017.8 1573.19  5018.1 1572.69  5021.9 1572.69  5022.2 1573.19
  5036.1 1573.54  5041.8 1575.62  5058.0 1576.74  5154.8 1577.16  5177.6 1578.23
  5189.0 1579.20  5205.2 1579.51  5243.2 1581.89  5257.3 1582.37  5280.1 1584.50
  5292.5 1586.45  5308.7 1587.77  5368.5 1589.59  5374.2 1590.36  5403.9 1592.25
#Mann=3,-1,0
  4729.6    0.05       0  5017.8    0.03       0  5022.2    0.05       0
Bank Sta=5017.8,5022.2
Exp/Cntr=0.3,0.1

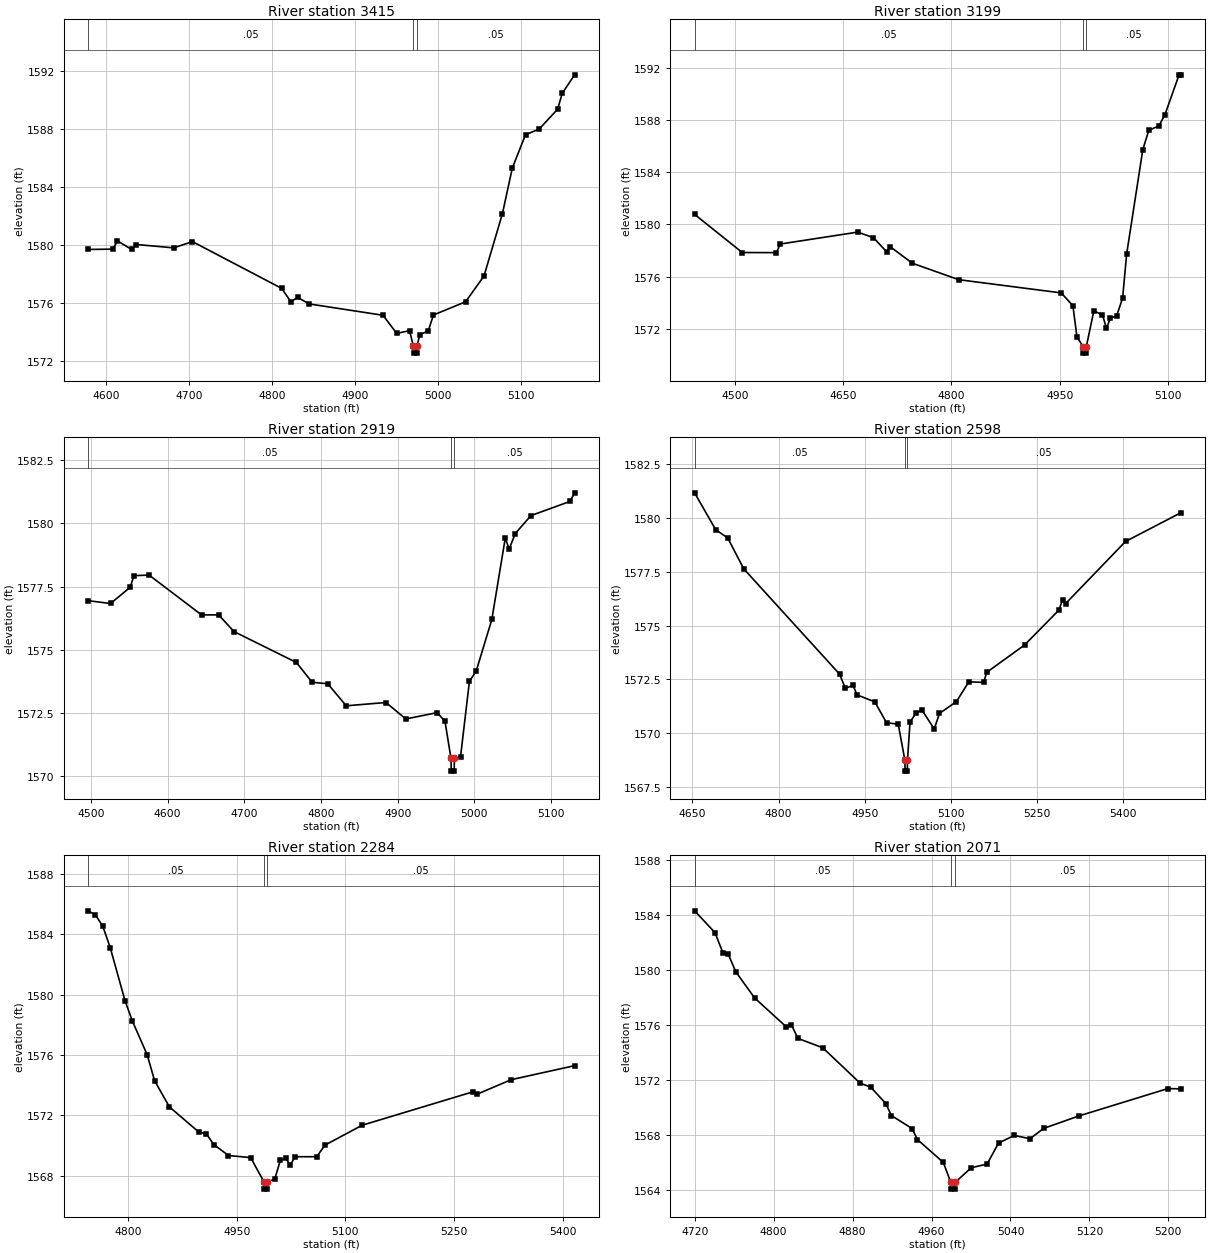
Type RM Length L Ch R = 1,3415,216,216,216
BEGIN DESCRIPTION:
Mapping XS e1e057ca
END DESCRIPTION:
XS GIS Cut Line= 3
      1621867.11      6937067.93      1622074.68      6936967.39
      1622237.60      6936651.23
#Sta/Elev= 30
  4578.0 1579.70  4607.8 1579.72  4613.4 1580.29  4630.4 1579.70  4636.0 1580.04
  4681.1 1579.81  4703.7 1580.24  4811.1 1577.02  4822.5 1576.09  4830.4 1576.39
  4844.7 1575.94  4933.4 1575.16  4949.9 1573.91  4965.4 1574.10  4969.9 1573.05
  4970.2 1572.55  4974.0 1572.55  4974.3 1573.05  4977.7 1573.81  4987.9 1574.09
  4994.2 1575.18  5032.9 1576.09  5055.1 1577.87  5077.3 1582.17  5089.2 1585.31
  5105.1 1587.61  5121.6 1588.00  5143.8 1589.37  5149.4 1590.47  5164.3 1591.74
#Mann=3,-1,0
  4578.0    0.05       0  4969.9    0.03       0  4974.3    0.05       0
Bank Sta=4969.9,4974.3
Exp/Cntr=0.3,0.1

Type RM Length L Ch R = 1,3199,280,280,280
BEGIN DESCRIPTION:
Deadman 03 7.0
END DESCRIPTION:
XS GIS Cut Line= 3
      1621786.96      6937157.87      1622305.00      6936938.00
      1622405.03      6936887.98
#Sta/Elev= 30
  4443.8 1580.76  4509.9 1577.84  4557.2 1577.83  4562.6 1578.49  4669.8 1579.40
  4691.8 1578.98  4710.0 1577.90  4715.4 1578.27  4745.8 1577.02  4810.1 1575.76
  4952.2 1574.75  4968.4 1573.77  4974.0 1571.38  4982.6 1570.64  4982.9 1570.14
  4986.7 1570.14  4987.0 1570.64  4997.4 1573.37  5009.4 1573.07  5014.9 1572.04
  5020.5 1572.84  5028.9 1572.97  5037.3 1574.35  5042.9 1577.72  5065.3 1585.71
  5073.6 1587.19  5087.6 1587.53  5096.0 1588.39  5115.6 1591.44  5118.4 1591.44
#Mann=3,-1,0
  4443.8    0.05       0  4982.6    0.03       0  4987.0    0.05       0
Bank Sta=4982.6,4987
Exp/Cntr=0.3,0.1

Type RM Length L Ch R = 1,2919,321,321,321
BEGIN DESCRIPTION:
Mapping XS d7ca8ba5
END DESCRIPTION:
XS GIS Cut Line= 3
      1621905.83      6937138.77      1622106.16      6937117.68
      1622530.98      6937199.70
#Sta/Elev= 30
  4496.5 1576.94  4525.8 1576.83  4551.3 1577.47  4556.3 1577.93  4576.1 1577.95
  4644.3 1576.38  4666.6 1576.38  4686.7 1575.72  4768.0 1574.50  4788.4 1573.72
  4808.8 1573.66  4832.9 1572.79  4884.7 1572.92  4910.6 1572.27  4951.4 1572.52
  4961.6 1572.18  4969.5 1570.71  4969.8 1570.21  4973.6 1570.21  4973.9 1570.71
  4981.9 1570.78  4993.5 1573.76  5002.3 1574.16  5022.7 1576.20  5040.2 1579.41
  5045.3 1578.98  5053.2 1579.59  5073.6 1580.30  5124.5 1580.86  5130.6 1581.20
#Mann=3,-1,0
  4496.5    0.05       0  4969.5    0.03       0  4973.9    0.05       0
Bank Sta=4969.5,4973.9
Exp/Cntr=0.3,0.1

Type RM Length L Ch R = 1,2598,314,314,314
BEGIN DESCRIPTION:
Deadman 03 6.0
END DESCRIPTION:
XS GIS Cut Line= 3
      1621818.54      6937284.15      1622291.98      6937388.31
      1622639.23      6937284.14
#Sta/Elev= 30
  4653.7 1581.17  4690.4 1579.46  4711.5 1579.07  4739.3 1577.64  4906.1 1572.75
  4916.3 1572.09  4929.6 1572.22  4936.8 1571.78  4967.5 1571.46  4988.0 1570.49
  5008.4 1570.42  5020.0 1568.74  5020.3 1568.24  5024.2 1568.24  5024.5 1568.74
  5028.9 1570.52  5039.2 1570.93  5049.4 1571.09  5071.1 1570.20  5080.1 1570.92
  5109.7 1571.47  5131.3 1572.39  5157.1 1572.36  5162.5 1572.83  5228.4 1574.10
  5287.8 1575.71  5294.6 1576.19  5299.8 1576.02  5404.2 1578.91  5501.0 1580.25
#Mann=3,-1,0
  4653.7    0.05       0  5020.0    0.03       0  5024.5    0.05       0
Bank Sta=5020,5024.5
Exp/Cntr=0.3,0.1

Type RM Length L Ch R = 1,2284,213,213,213
BEGIN DESCRIPTION:
Deadman 03 5.0
END DESCRIPTION:
XS GIS Cut Line= 3
      1621805.05      6937588.01      1622055.00      6937638.00
      1622460.16      6937541.50
#Sta/Elev= 30
  4745.0 1585.56  4755.1 1585.29  4765.3 1584.53  4775.5 1583.12  4795.9 1579.60
  4806.1 1578.25  4826.5 1576.01  4836.7 1574.30  4857.1 1572.56  4897.9 1570.88
  4908.1 1570.78  4918.3 1570.06  4938.7 1569.33  4969.3 1569.19  4987.5 1567.60
  4987.8 1567.10  4991.7 1567.10  4992.0 1567.60  5002.5 1567.75  5010.2 1569.00
  5018.4 1569.15  5023.5 1568.67  5030.7 1569.25  5060.5 1569.25  5071.9 1570.02
  5123.3 1571.34  5276.4 1573.56  5281.5 1573.39  5328.9 1574.36  5416.4 1575.29
#Mann=3,-1,0
  4745.0    0.05       0  4987.5    0.03       0  4992.0    0.05       0
Bank Sta=4987.5,4992
Exp/Cntr=0.3,0.1

Type RM Length L Ch R = 1,2071,246,246,246
BEGIN DESCRIPTION:
Mapping XS ba1f7f13
END DESCRIPTION:
XS GIS Cut Line= 3
      1621815.37      6937902.82      1622067.87      6937820.76
      1622266.74      6937710.27
#Sta/Elev= 30
  4719.9 1584.32  4740.5 1582.74  4748.7 1581.25  4754.0 1581.17  4761.6 1579.89
  4780.7 1577.98  4812.6 1575.89  4817.9 1576.03  4824.7 1575.03  4849.8 1574.35
  4887.7 1571.77  4898.3 1571.49  4913.7 1570.29  4919.3 1569.42  4940.3 1568.47
  4945.7 1567.67  4971.9 1566.01  4979.5 1564.56  4979.8 1564.06  4983.7 1564.06
  4984.1 1564.56  5000.3 1565.62  5016.3 1565.88  5027.9 1567.41  5043.8 1567.97
  5059.8 1567.73  5073.6 1568.48  5109.0 1569.38  5199.5 1571.38  5212.9 1571.36
#Mann=3,-1,0
  4719.9    0.05       0  4979.5    0.03       0  4984.1    0.05       0
Bank Sta=4979.5,4984.1
Exp/Cntr=0.3,0.1

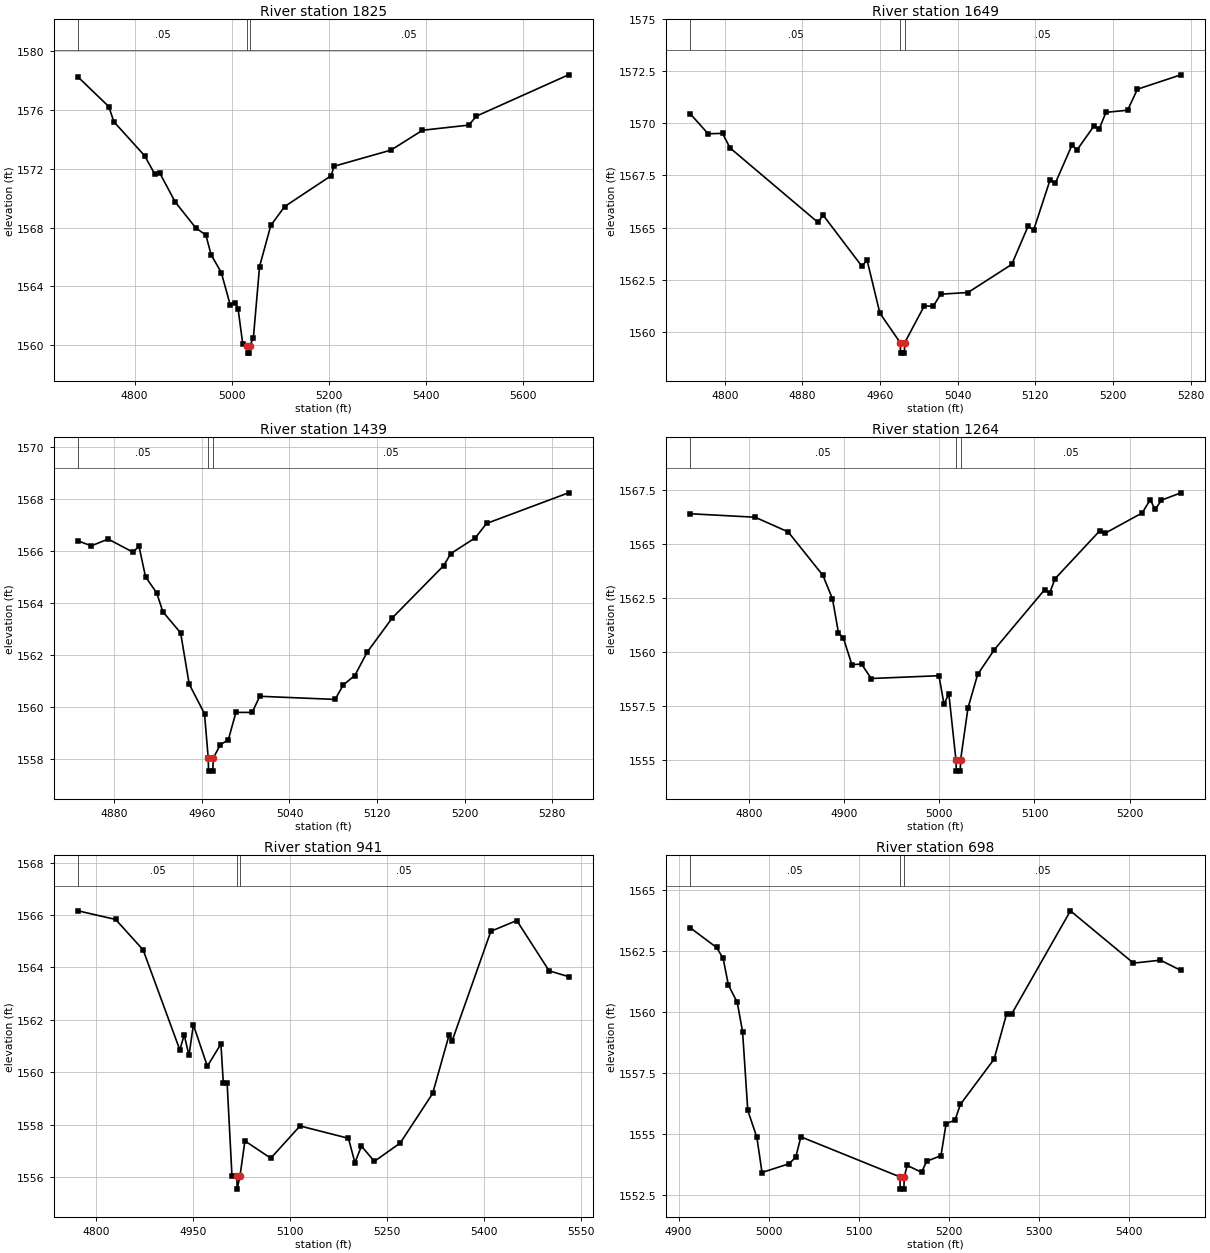
Type RM Length L Ch R = 1,1825,176,176,176
BEGIN DESCRIPTION:
Deadman 03 4.0
END DESCRIPTION:
XS GIS Cut Line= 3
      1621954.98      6938088.01      1622255.00      6937988.00
      1622605.01      6937387.97
#Sta/Elev= 30
  4683.6 1578.24  4746.9 1576.23  4757.4 1575.20  4820.7 1572.89  4841.7 1571.64
  4852.3 1571.69  4883.9 1569.74  4926.1 1567.98  4947.1 1567.49  4957.7 1566.16
  4978.8 1564.94  4997.2 1562.74  5007.7 1562.88  5013.5 1562.45  5023.0 1560.10
  5032.7 1559.96  5033.0 1559.46  5036.9 1559.46  5037.3 1559.96  5044.9 1560.48
  5057.7 1565.35  5080.9 1568.15  5109.4 1569.43  5205.3 1571.53  5211.1 1572.17
  5328.6 1573.27  5393.5 1574.62  5489.0 1574.97  5504.7 1575.58  5694.5 1578.39
#Mann=3,-1,0
  4683.6    0.05       0  5032.7    0.03       0  5037.3    0.05       0
Bank Sta=5032.7,5037.3
Exp/Cntr=0.3,0.1

Type RM Length L Ch R = 1,1649,210,210,210
BEGIN DESCRIPTION:
Mapping XS 9ed13df4
END DESCRIPTION:
XS GIS Cut Line= 3
      1622175.16      6938221.66      1622351.96      6938136.41
      1622487.67      6937858.67
#Sta/Elev= 30
  4764.7 1570.45  4782.9 1569.50  4797.8 1569.52  4805.5 1568.82  4896.0 1565.25
  4901.5 1565.59  4941.2 1563.15  4946.8 1563.42  4959.9 1560.89  4980.9 1559.47
  4981.2 1558.97  4985.1 1558.97  4985.5 1559.47  5005.7 1561.24  5014.9 1561.22
  5022.6 1561.80  5050.7 1561.88  5095.8 1563.23  5112.7 1565.07  5118.3 1564.87
  5135.2 1567.27  5140.8 1567.14  5157.7 1568.94  5163.3 1568.74  5180.3 1569.86
  5185.8 1569.72  5192.9 1570.53  5215.2 1570.63  5225.3 1571.64  5270.1 1572.33
#Mann=3,-1,0
  4764.7    0.05       0  4980.9    0.03       0  4985.5    0.05       0
Bank Sta=4980.9,4985.5
Exp/Cntr=0.3,0.1

Type RM Length L Ch R = 1,1439,175,175,175
BEGIN DESCRIPTION:
Deadman 03 3.0
END DESCRIPTION:
XS GIS Cut Line= 3
      1622390.91      6938329.61      1622512.54      6938263.12
      1622635.78      6937979.34
#Sta/Elev= 30
  4846.9 1566.38  4859.0 1566.19  4874.4 1566.45  4896.9 1565.95  4902.6 1566.17
  4908.5 1565.00  4918.7 1564.38  4924.4 1563.65  4940.6 1562.84  4948.4 1560.87
  4962.4 1559.73  4965.8 1558.02  4966.1 1557.52  4970.0 1557.52  4970.4 1558.02
  4976.9 1558.54  4984.1 1558.72  4991.1 1559.78  5005.9 1559.78  5012.9 1560.40
  5081.7 1560.28  5089.2 1560.84  5099.7 1561.20  5111.0 1562.10  5134.0 1563.42
  5180.9 1565.43  5187.3 1565.89  5209.8 1566.50  5220.0 1567.05  5294.9 1568.23
#Mann=3,-1,0
  4846.9    0.05       0  4965.8    0.03       0  4970.4    0.05       0
Bank Sta=4965.8,4970.4
Exp/Cntr=0.3,0.1

Type RM Length L Ch R = 1,1264,323,323,323
BEGIN DESCRIPTION:
Mapping XS aed4e586
END DESCRIPTION:
XS GIS Cut Line= 2
      1622631.48      6938544.84      1622725.22      6938037.93
#Sta/Elev= 30
  4738.4 1566.41  4806.4 1566.25  4841.1 1565.57  4877.6 1563.56  4887.7 1562.47
  4894.0 1560.89  4899.1 1560.66  4908.1 1559.42  4918.2 1559.45  4928.4 1558.78
  4999.6 1558.91  5004.9 1557.59  5010.0 1558.07  5017.5 1554.99  5017.9 1554.49
  5022.0 1554.49  5022.3 1554.99  5030.1 1557.41  5040.3 1558.97  5057.9 1560.12
  5110.8 1562.90  5115.9 1562.73  5121.6 1563.40  5168.8 1565.63  5173.9 1565.50
  5213.2 1566.45  5221.7 1567.06  5226.8 1566.61  5233.5 1567.04  5253.9 1567.38
#Mann=3,-1,0
  4738.4    0.05       0  5017.5    0.03       0  5022.3    0.05       0
Bank Sta=5017.5,5022.3
Exp/Cntr=0.3,0.1

Type RM Length L Ch R = 1,941,243,243,243
BEGIN DESCRIPTION:
Deadman 03 2.0
END DESCRIPTION:
XS GIS Cut Line= 3
      1622700.91      6938655.99      1622855.00      6938488.00
      1622878.00      6937958.05
#Sta/Elev= 30
  4772.6 1566.16  4830.7 1565.83  4873.2 1564.67  4930.0 1560.85  4936.7 1561.43
  4944.1 1560.64  4950.9 1561.81  4972.5 1560.23  4993.5 1561.08  4997.2 1559.59
  5003.1 1559.59  5010.6 1556.04  5018.2 1556.04  5018.5 1555.54  5023.0 1556.04
  5030.6 1557.38  5070.6 1556.72  5115.8 1557.95  5190.7 1557.48  5200.7 1556.55
  5210.8 1557.18  5230.8 1556.60  5270.8 1557.30  5320.9 1559.19  5346.2 1561.41
  5351.2 1561.21  5410.9 1565.38  5451.0 1565.79  5501.0 1563.87  5531.0 1563.65
#Mann=3,-1,0
  4772.6    0.05       0  5018.2    0.03       0  5023.0    0.05       0
Bank Sta=5018.2,5023
Exp/Cntr=0.3,0.1

Type RM Length L Ch R = 1,698,197,197,197
BEGIN DESCRIPTION:
Mapping XS a0fa22e5
END DESCRIPTION:
XS GIS Cut Line= 3
      1623068.80      6938443.17      1622892.01      6938133.39
      1622895.26      6937945.29
#Sta/Elev= 30
  4913.2 1563.43  4942.2 1562.63  4949.5 1562.19  4955.3 1561.10  4965.2 1560.38
  4971.1 1559.19  4976.9 1555.96  4987.0 1554.86  4992.7 1553.42  5022.8 1553.78
  5030.2 1554.05  5035.9 1554.88  5145.9 1553.24  5146.2 1552.74  5150.3 1552.74
  5150.7 1553.24  5154.0 1553.71  5169.9 1553.43  5175.6 1553.88  5191.5 1554.11
  5197.2 1555.42  5207.0 1555.56  5213.1 1556.21  5250.5 1558.06  5264.3 1559.90
  5269.9 1559.90  5335.3 1564.13  5405.3 1561.99  5435.3 1562.11  5458.0 1561.69
#Mann=3,-1,0
  4913.2    0.05       0  5145.9    0.05       0  5150.7    0.05       0
Bank Sta=5145.9,5150.7
Exp/Cntr=0.3,0.1

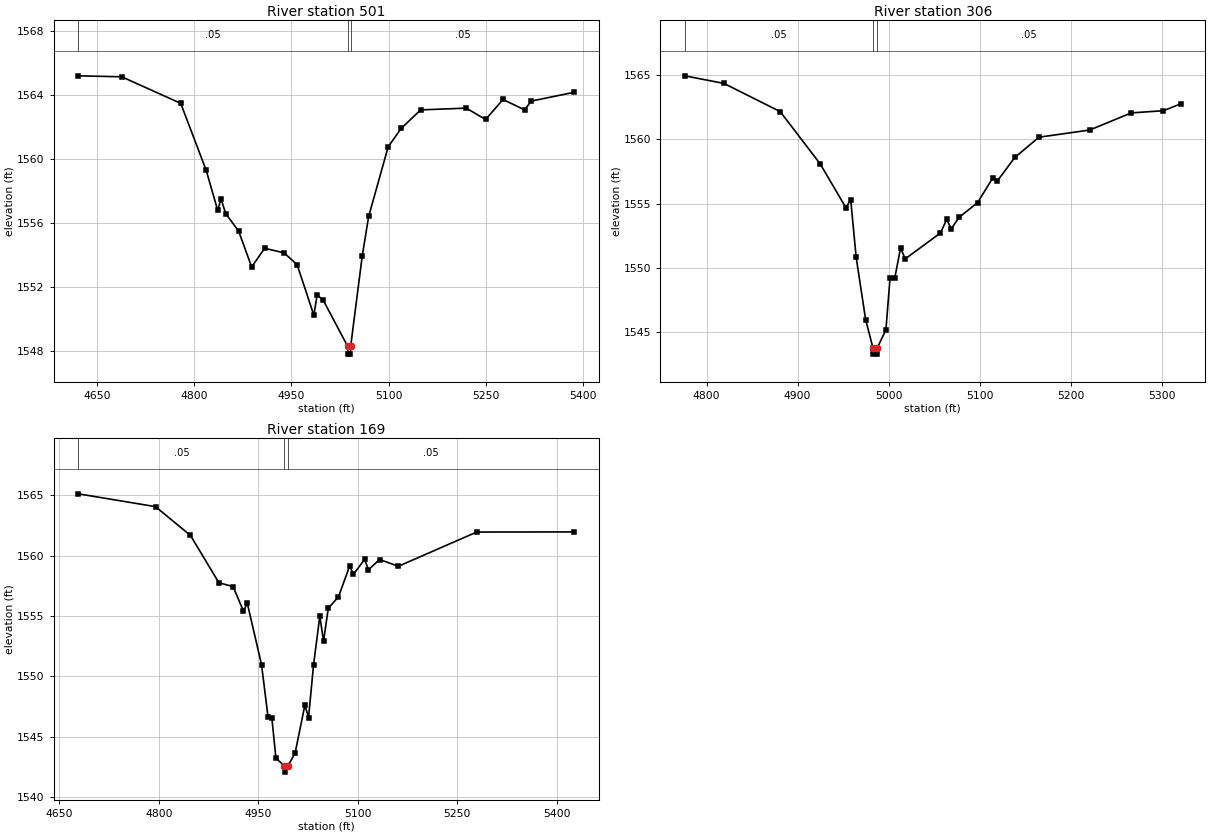
Type RM Length L Ch R = 1,501,195,195,195
BEGIN DESCRIPTION:
Mapping XS ef47a993
END DESCRIPTION:
XS GIS Cut Line= 3
      1623107.41      6938574.86      1623114.39      6938421.33
      1623072.59      6937811.85
#Sta/Elev= 30
  4621.6 1565.19  4688.5 1565.13  4779.5 1563.47  4818.7 1559.29  4836.6 1556.77
  4841.6 1557.51  4848.8 1556.58  4868.8 1555.48  4888.9 1553.24  4908.9 1554.41
  4939.0 1554.12  4959.0 1553.38  4984.8 1550.22  4989.8 1551.48  4999.1 1551.17
  5036.8 1548.29  5037.2 1547.79  5041.3 1547.79  5041.6 1548.29  5059.3 1553.90
  5069.3 1556.40  5099.4 1560.75  5119.4 1561.90  5149.5 1563.06  5219.7 1563.17
  5249.7 1562.46  5276.4 1563.71  5309.9 1563.06  5319.9 1563.61  5386.2 1564.16
#Mann=3,-1,0
  4621.6    0.05       0  5036.8    0.05       0  5041.6    0.05       0
Bank Sta=5036.8,5041.6
Exp/Cntr=0.3,0.1

Type RM Length L Ch R = 1,306,137,137,137
BEGIN DESCRIPTION:
Mapping XS 3372bf70
END DESCRIPTION:
XS GIS Cut Line= 3
      1623179.29      6938538.71      1623242.54      6938321.53
      1623179.29      6938009.48
#Sta/Elev= 30
  4776.1 1564.93  4819.1 1564.34  4880.9 1562.15  4924.8 1558.09  4953.1 1554.68
  4958.3 1555.32  4964.3 1550.85  4974.7 1546.00  4982.7 1543.81  4983.1 1543.31
  4987.3 1543.31  4987.6 1543.81  4997.0 1545.19  5001.5 1549.21  5006.7 1549.21
  5013.1 1551.56  5018.2 1550.71  5056.9 1552.72  5063.7 1553.77  5068.8 1553.05
  5077.3 1553.93  5097.7 1555.08  5114.4 1557.00  5119.5 1556.77  5138.6 1558.59
  5165.1 1560.16  5220.9 1560.72  5266.4 1562.05  5301.8 1562.22  5320.7 1562.75
#Mann=3,-1,0
  4776.1    0.05       0  4982.7    0.05       0  4987.6    0.05       0
Bank Sta=4982.7,4987.6
Exp/Cntr=0.3,0.1

Type RM Length L Ch R = 1,169,0,0,0
BEGIN DESCRIPTION:
Deadman 03 1.0
END DESCRIPTION:
XS GIS Cut Line= 3
      1623211.33      6938614.32      1623378.00      6938333.07
      1623193.96      6937954.57
#Sta/Elev= 30
  4678.5 1565.10  4794.9 1564.04  4847.6 1561.66  4890.5 1557.75  4911.9 1557.43
  4927.5 1555.41  4933.3 1556.06  4954.8 1550.98  4964.6 1546.65  4970.4 1546.54
  4976.5 1543.25  4989.4 1542.59  4989.7 1542.09  4994.3 1542.59  5005.4 1543.65
  5020.2 1547.64  5025.7 1546.60  5033.3 1550.98  5042.7 1554.99  5048.3 1552.92
  5055.5 1555.64  5070.8 1556.58  5087.8 1559.14  5093.4 1558.44  5110.4 1559.69
  5116.0 1558.82  5132.9 1559.67  5161.1 1559.11  5279.4 1561.94  5426.3 1561.95
#Mann=3,-1,0
  4678.5    0.05       0  4989.4    0.05       0  4994.3    0.05       0
Bank Sta=4989.4,4994.3
Exp/Cntr=0.3,0.1

Chan Stop Cuts=-1