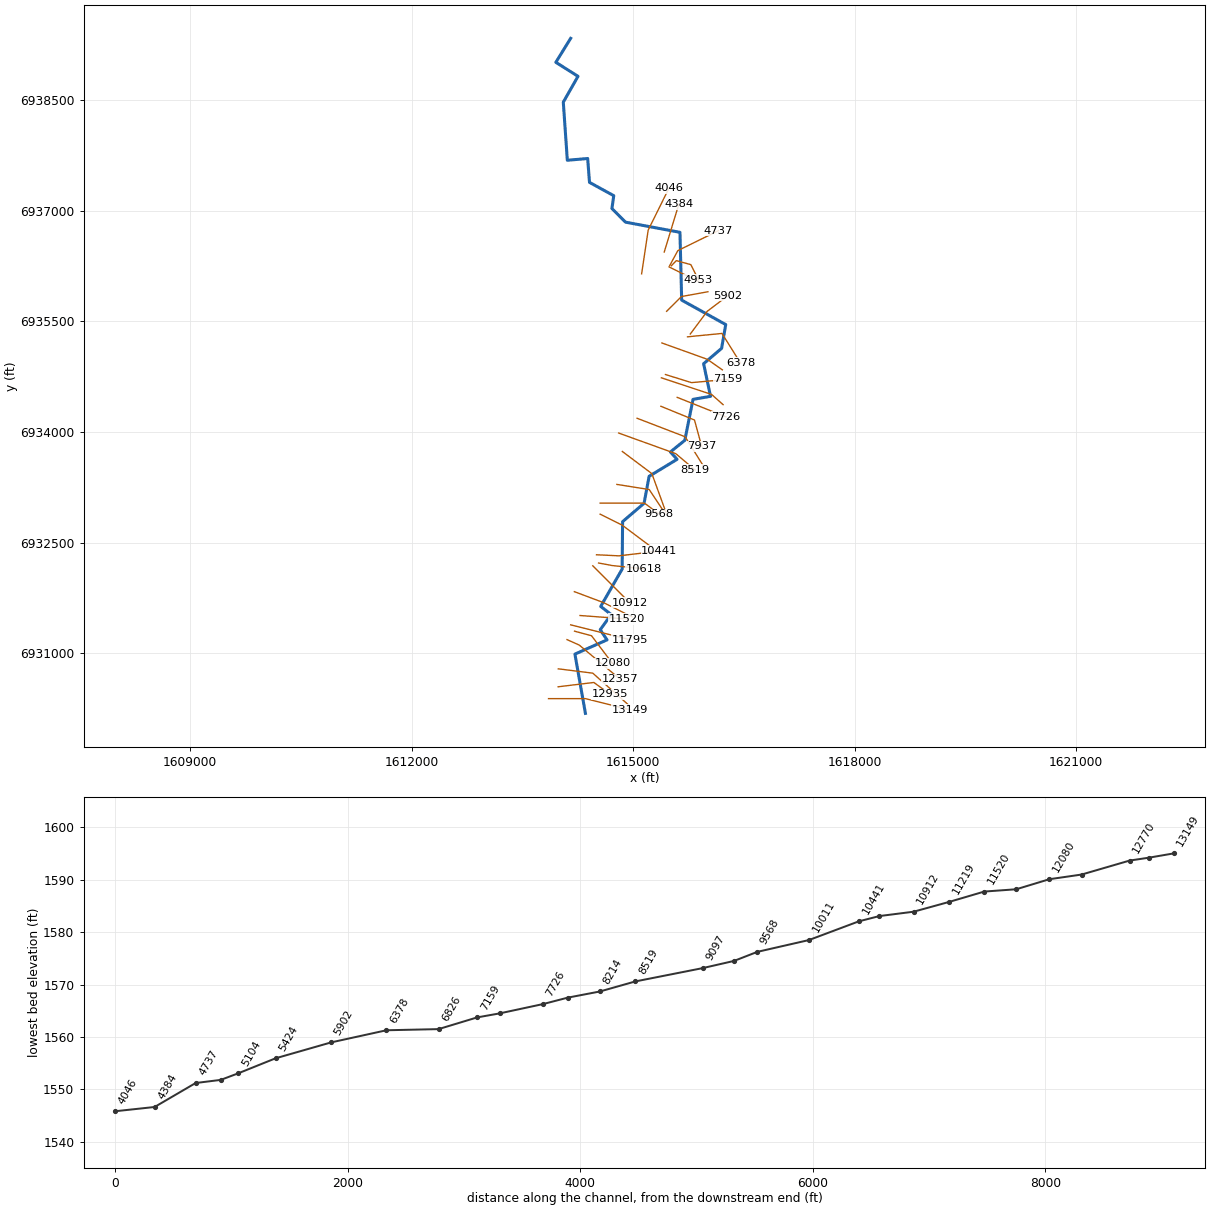
--- Deadman 04.prj (project) ---

Proj Title=Deadman 04 Base Level Engineering
Current Plan=p01
Default Exp/Contr=0.3,0.1
English Units
Geom File=g01
Flow File=f01
Plan File=p01
BEGIN DESCRIPTION:
Deadman 04
END DESCRIPTION:

--- Deadman 04.p01 (plan) ---

Plan Title=Multiple Run
Short Identifier=Multiple
Geom File=g01
Flow File=f01
Subcritical Flow
K Sum by GR= 0
Std Step Tol= 0.01
Critical Tol= 0.01
Num of Std Step Trials= 20
Max Error Tol= 0.3
Flow Tol Ratio= 0.001
Split Flow NTrial= 30
Split Flow Tol= 0.02
Split Flow Ratio= 0.02
Log Output Level= 0
Friction Slope Method= 1
Unsteady Friction Slope Method= 2
Unsteady Bridges Friction Slope Method= 1
Parabolic Critical Depth
Global Vel Dist=  1 , 1 , 1
Global Log Level= 0
CheckData=True
Encroach Param= -1, 0, 0, 0
BEGIN DESCRIPTION:
Multiple Run
END DESCRIPTION:

--- Deadman 04.f01 (steady flow) ---

Flow Title=Multiple
Number of Profiles=7
Profile Names=10-year,25-year,50-year,1pct_min,100-year,1pct_plu,500-year
River Rch & RM= Deadman 04,Reach-1,13149
     344     483     599     370     739    1474    1136
River Rch & RM= Deadman 04,Reach-1,4737
     441     627     784     487     972    1940    1517
Boundary for River Rch & Prof#=Deadman 04,Reach-1,1
Up Type=0
Dn Type=3
Dn Slope=0.005
Boundary for River Rch & Prof#=Deadman 04,Reach-1,2
Up Type=0
Dn Type=3
Dn Slope=0.005
Boundary for River Rch & Prof#=Deadman 04,Reach-1,3
Up Type=0
Dn Type=3
Dn Slope=0.005
Boundary for River Rch & Prof#=Deadman 04,Reach-1,4
Up Type=0
Dn Type=3
Dn Slope=0.005
Boundary for River Rch & Prof#=Deadman 04,Reach-1,5
Up Type=0
Dn Type=3
Dn Slope=0.005
Boundary for River Rch & Prof#=Deadman 04,Reach-1,6
Up Type=0
Dn Type=3
Dn Slope=0.005
Boundary for River Rch & Prof#=Deadman 04,Reach-1,7
Up Type=0
Dn Type=3
Dn Slope=0.005

--- Deadman 04.g01 (geometry) ---

Geom Title=Existing Conditions

River Reach=Deadman 04,Reach-1
Reach XY= 30
      1614355.00      6930188.00      1614212.84      6930991.24
      1614647.52      6931184.38      1614555.17      6931321.96
      1614704.13      6931527.67      1614561.98      6931637.80
      1614852.78      6932143.94      1614858.54      6932786.54
      1615149.48      6933035.56      1615217.95      6933401.64
      1615596.09      6933631.48      1615506.35      6933731.75
      1615701.47      6933889.45      1615812.70      6934444.57
      1616049.71      6934485.25      1615955.97      6934927.71
      1616199.54      6935135.55      1616255.70      6935458.16
      1615658.75      6935789.55      1615635.54      6936708.54
      1614898.94      6936846.14      1614714.13      6937031.26
      1614738.75      6937205.13      1614410.36      6937385.30
      1614385.40      6937709.15      1614109.97      6937685.41
      1614055.31      6938472.96      1614254.64      6938823.11
      1613954.36      6939013.00      1614155.00      6939338.00

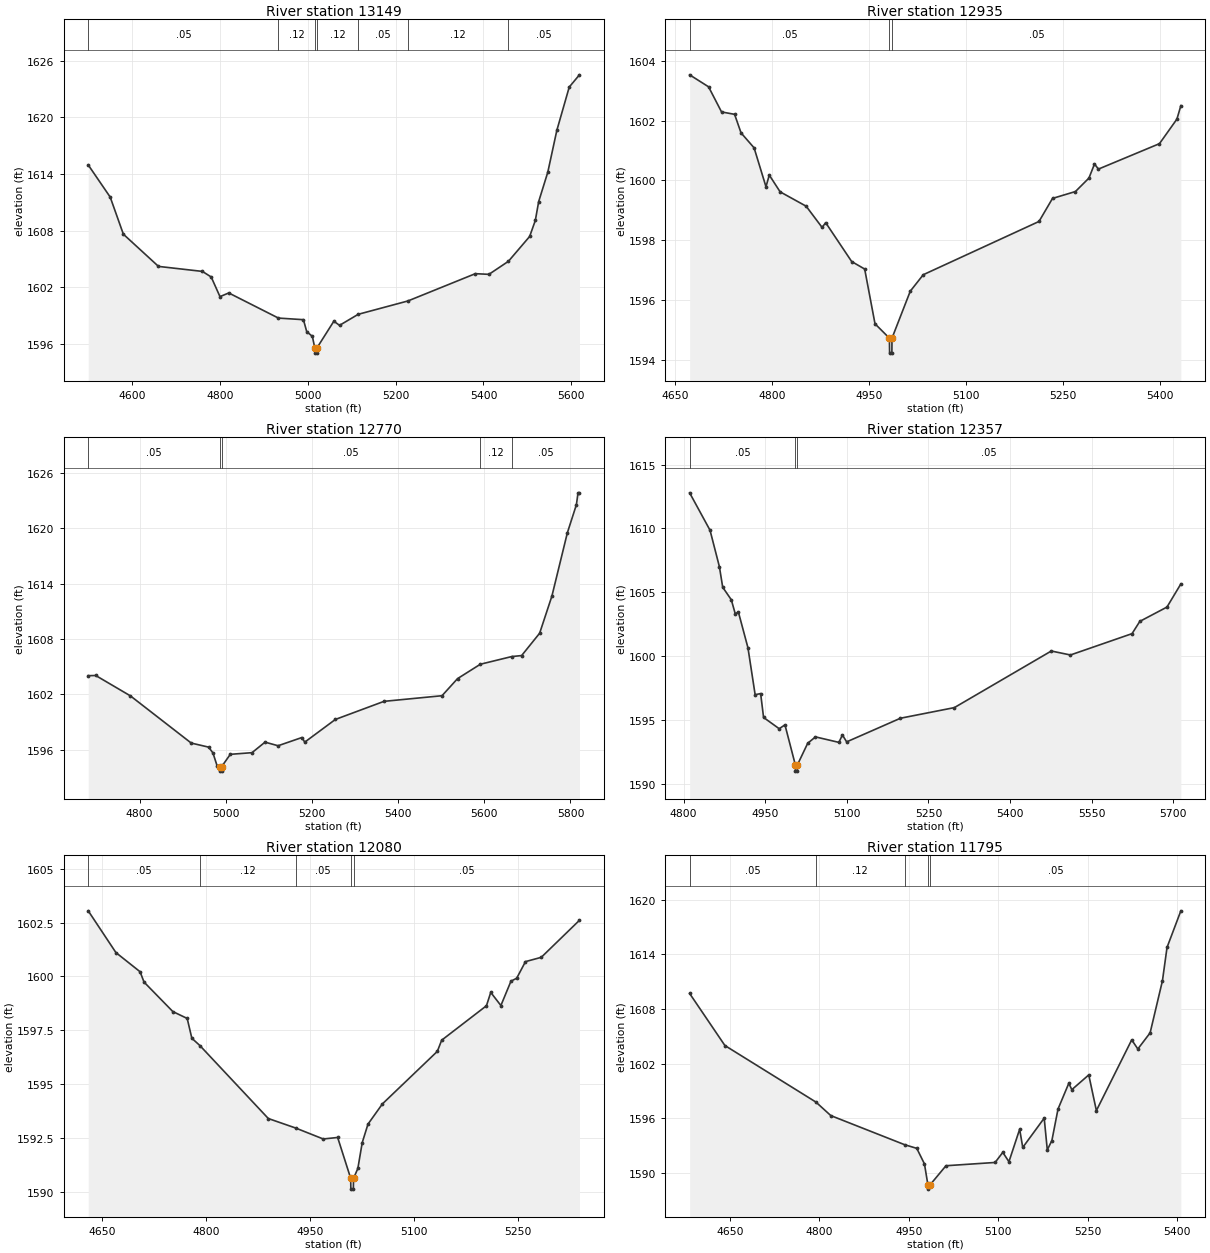
Type RM Length L Ch R = 1,13149,214,214,214
BEGIN DESCRIPTION:
Deadman 04 26.0
END DESCRIPTION:
XS GIS Cut Line= 3
      1613854.96      6930388.00      1614355.00      6930388.00
      1614954.99      6930238.00
#Sta/Elev= 30
  4500.0 1614.97  4550.0 1611.57  4580.0 1607.64  4660.0 1604.23  4760.0 1603.70
  4780.0 1603.11  4800.0 1601.03  4820.0 1601.42  4933.1 1598.76  4990.0 1598.59
  4997.5 1597.33  5010.4 1596.82  5016.1 1595.55  5016.3 1595.05  5019.8 1595.05
  5020.1 1595.55  5059.3 1598.43  5072.2 1597.99  5114.8 1599.16  5227.8 1600.57
  5381.4 1603.46  5412.4 1603.39  5456.8 1604.77  5505.1 1607.40  5518.0 1609.09
  5525.7 1611.10  5546.4 1614.20  5567.0 1618.63  5595.3 1623.22  5618.5 1624.51
#Mann=7,-1,0
  4500.0    0.05       0  4933.1    0.12       0  5016.1    0.07       0
  5020.1    0.12       0  5114.8    0.05       0  5227.8    0.12       0
  5456.8    0.05       0
Bank Sta=5016.1,5020.1
Exp/Cntr=0.3,0.1

Type RM Length L Ch R = 1,12935,165,165,165
BEGIN DESCRIPTION:
Mapping XS cda9ea10
END DESCRIPTION:
XS GIS Cut Line= 3
      1613985.93      6930548.37      1614469.00      6930606.93
      1614691.14      6930446.69
#Sta/Elev= 30
  4672.5 1603.53  4701.8 1603.13  4721.9 1602.29  4742.1 1602.21  4752.1 1601.59
  4772.3 1601.09  4790.7 1599.79  4795.8 1600.18  4812.6 1599.62  4852.9 1599.14
  4877.6 1598.43  4883.1 1598.59  4923.4 1597.29  4943.5 1597.04  4959.5 1595.21
  4981.8 1594.73  4982.1 1594.23  4985.6 1594.23  4985.8 1594.73  5014.1 1596.30
  5034.2 1596.85  5213.4 1598.63  5234.3 1599.40  5269.8 1599.63  5290.7 1600.08
  5299.3 1600.55  5305.4 1600.38  5399.9 1601.23  5426.9 1602.05  5433.0 1602.50
#Mann=3,-1,0
  4672.5    0.05       0  4981.8    0.05       0  4985.8    0.05       0
Bank Sta=4981.8,4985.8
Exp/Cntr=0.3,0.1

Type RM Length L Ch R = 1,12770,413,413,413
BEGIN DESCRIPTION:
Deadman 04 25.0
END DESCRIPTION:
XS GIS Cut Line= 3
      1613987.75      6930791.75      1614454.36      6930733.19
      1614954.98      6930288.02
#Sta/Elev= 30
  4680.6 1604.02  4698.0 1604.04  4778.6 1601.83  4919.7 1596.72  4960.0 1596.28
  4970.1 1595.65  4980.2 1594.19  4986.5 1594.18  4986.8 1593.68  4990.3 1593.68
  4990.5 1594.18  5010.4 1595.50  5060.8 1595.68  5091.0 1596.82  5121.3 1596.43
  5176.5 1597.32  5183.2 1596.82  5254.3 1599.28  5367.2 1601.24  5501.8 1601.85
  5537.8 1603.70  5590.8 1605.26  5663.4 1606.09  5686.6 1606.20  5728.4 1608.62
  5756.9 1612.65  5792.8 1619.51  5813.7 1622.54  5817.5 1623.83  5820.8 1623.83
#Mann=5,-1,0
  4680.6    0.05       0  4986.5    0.05       0  4990.5    0.05       0
  5590.8    0.12       0  5663.4    0.05       0
Bank Sta=4986.5,4990.5
Exp/Cntr=0.3,0.1

Type RM Length L Ch R = 1,12357,277,277,277
BEGIN DESCRIPTION:
Deadman 04 24.0
END DESCRIPTION:
XS GIS Cut Line= 3
      1614105.03      6931187.99      1614271.36      6931113.82
      1614824.56      6930651.91
#Sta/Elev= 30
  4811.0 1612.79  4848.5 1609.86  4865.7 1607.01  4871.8 1605.40  4887.6 1604.42
  4895.0 1603.30  4900.5 1603.48  4918.2 1600.66  4931.4 1596.99  4941.5 1597.08
  4946.9 1595.21  4975.6 1594.33  4986.2 1594.63  5005.2 1591.51  5005.4 1591.01
  5008.9 1591.01  5009.2 1591.51  5028.0 1593.19  5042.3 1593.69  5085.3 1593.26
  5091.8 1593.84  5099.6 1593.30  5198.5 1595.15  5297.5 1595.98  5475.7 1600.41
  5510.9 1600.10  5624.1 1601.77  5638.4 1602.73  5688.3 1603.85  5713.8 1605.66
#Mann=3,-1,0
  4811.0    0.05       0  5005.2    0.03       0  5009.2    0.05       0
Bank Sta=5005.2,5009.2
Exp/Cntr=0.3,0.1

Type RM Length L Ch R = 1,12080,285,285,285
BEGIN DESCRIPTION:
Mapping XS 9cd707c2
END DESCRIPTION:
XS GIS Cut Line= 3
      1614207.36      6931302.30      1614437.89      6931240.09
      1614720.76      6930865.97
#Sta/Elev= 30
  4630.3 1603.05  4670.2 1601.11  4705.0 1600.22  4710.7 1599.74  4752.2 1598.37
  4772.9 1598.05  4779.6 1597.13  4791.2 1596.79  4889.8 1593.40  4929.1 1592.96
  4968.9 1592.45  4989.7 1592.52  5008.5 1590.62  5008.7 1590.12  5012.3 1590.12
  5012.6 1590.62  5018.8 1591.08  5025.1 1592.28  5033.4 1593.14  5054.2 1594.08
  5133.3 1596.52  5139.6 1597.04  5204.1 1598.64  5210.3 1599.26  5224.9 1598.65
  5239.4 1599.78  5247.7 1599.92  5260.3 1600.69  5283.1 1600.89  5338.1 1602.61
#Mann=5,-1,0
  4630.3    0.05       0  4791.2    0.12       0  4929.1    0.05       0
  5008.5    0.05       0  5012.6    0.05       0
Bank Sta=5008.5,5012.6
Exp/Cntr=0.3,0.1

Type RM Length L Ch R = 1,11795,275,275,275
BEGIN DESCRIPTION:
Deadman 04 23.0
END DESCRIPTION:
XS GIS Cut Line= 3
      1614155.04      6931387.99      1614555.00      6931288.00
      1614955.02      6931187.99
#Sta/Elev= 30
  4582.0 1609.70  4641.2 1603.98  4793.9 1597.77  4819.0 1596.28  4943.0 1593.08
  4963.3 1592.68  4976.2 1590.97  4981.9 1588.70  4982.2 1588.20  4986.0 1588.70
  5012.3 1590.77  5094.8 1591.13  5107.7 1592.24  5118.0 1591.21  5136.0 1594.78
  5141.2 1592.78  5177.2 1596.00  5182.4 1592.51  5190.1 1593.54  5200.4 1597.00
  5218.5 1599.83  5223.6 1599.13  5252.0 1600.75  5264.8 1596.83  5324.1 1604.60
  5334.4 1603.60  5355.0 1605.37  5375.7 1611.10  5383.4 1614.76  5406.6 1618.78
#Mann=5,-1,0
  4582.0    0.05       0  4793.9    0.12       0  4943.0    0.05       0
  4981.9    0.05       0  4986.0    0.05       0
Bank Sta=4981.9,4986
Exp/Cntr=0.3,0.1

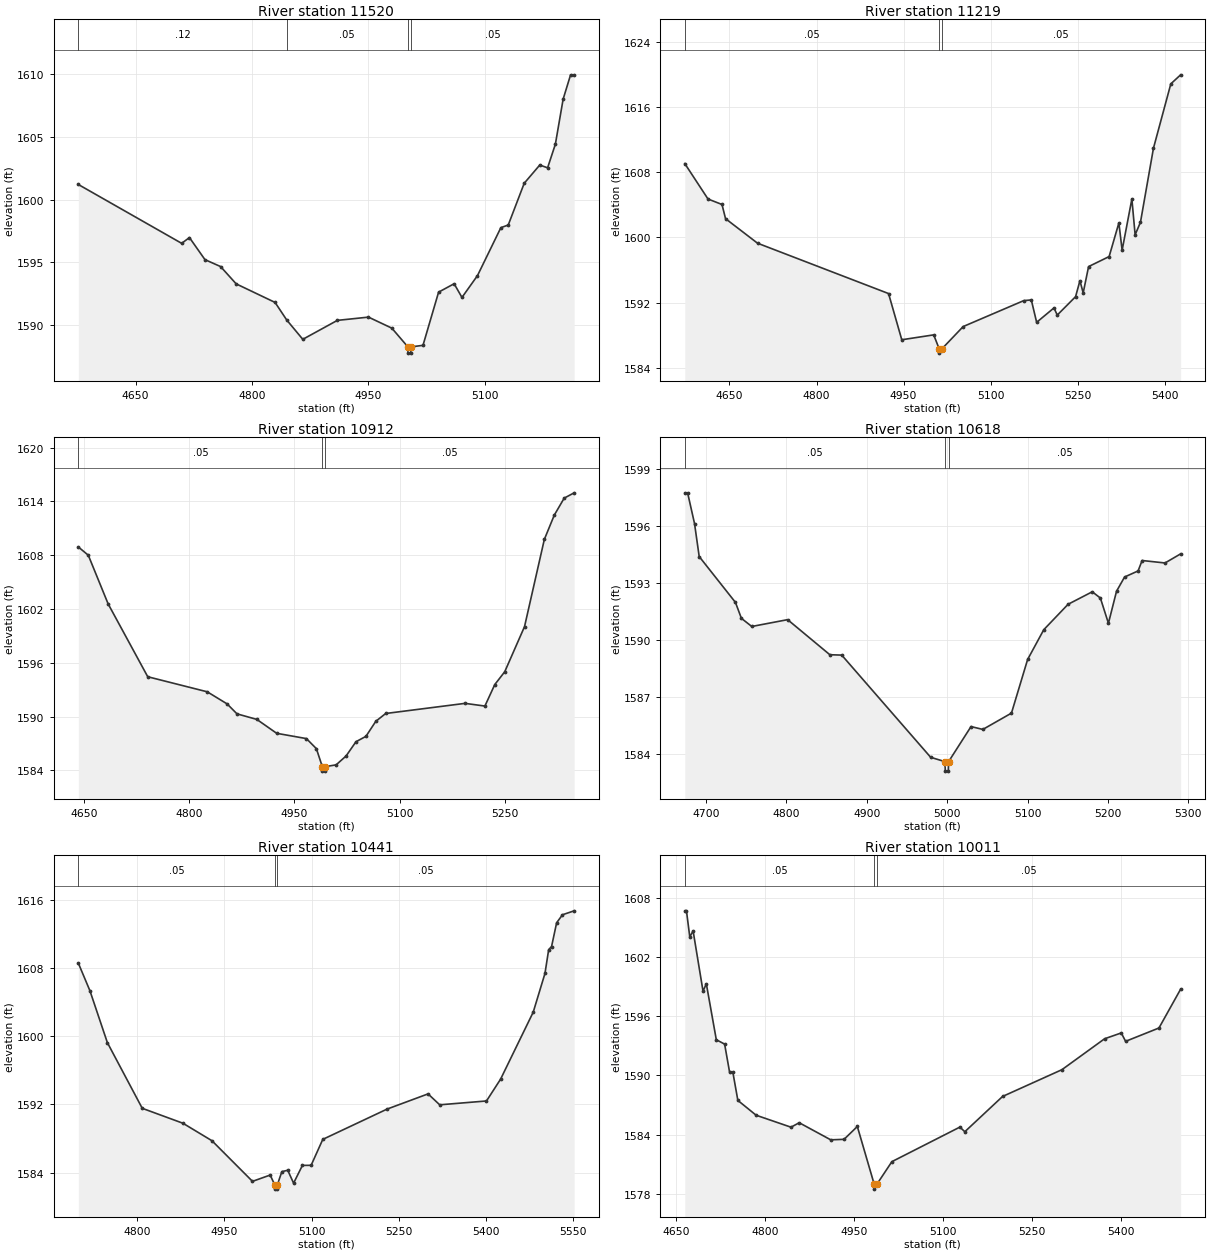
Type RM Length L Ch R = 1,11520,301,301,301
BEGIN DESCRIPTION:
Mapping XS eedd6eb5
END DESCRIPTION:
XS GIS Cut Line= 2
      1614282.31      6931514.59      1614919.13      6931467.01
#Sta/Elev= 30
  4576.3 1601.20  4709.4 1596.51  4719.4 1596.97  4739.4 1595.21  4759.5 1594.66
  4779.6 1593.28  4829.7 1591.80  4844.7 1590.40  4865.4 1588.86  4909.9 1590.37
  4950.0 1590.63  4980.1 1589.75  5000.7 1588.26  5000.9 1587.76  5004.5 1587.76
  5004.8 1588.26  5020.2 1588.38  5040.3 1592.62  5060.3 1593.29  5070.4 1592.20
  5090.4 1593.94  5120.5 1597.76  5130.0 1597.97  5150.6 1601.30  5170.6 1602.75
  5180.7 1602.53  5190.7 1604.41  5200.7 1608.00  5210.3 1609.94  5214.9 1609.94
#Mann=4,-1,0
  4576.3    0.12       0  4844.7    0.05       0  5000.7    0.05       0
  5004.8    0.05       0
Bank Sta=5000.7,5004.8
Exp/Cntr=0.3,0.1

Type RM Length L Ch R = 1,11219,307,307,307
BEGIN DESCRIPTION:
Deadman 04 22.0
END DESCRIPTION:
XS GIS Cut Line= 3
      1614205.04      6931837.99      1614602.58      6931688.43
      1614986.88      6931496.28
#Sta/Elev= 30
  4573.0 1609.05  4613.0 1604.70  4637.1 1604.03  4643.2 1602.29  4698.3 1599.28
  4924.1 1593.10  4946.9 1587.43  5001.9 1588.03  5011.5 1586.29  5011.8 1585.79
  5015.7 1586.29  5052.7 1589.05  5157.0 1592.23  5170.1 1592.32  5179.3 1589.57
  5209.2 1591.34  5214.8 1590.46  5246.4 1592.72  5253.9 1594.68  5259.5 1593.18
  5268.8 1596.41  5304.2 1597.64  5321.0 1601.77  5326.6 1598.42  5343.4 1604.71
  5349.0 1600.31  5358.2 1601.85  5380.6 1610.94  5410.5 1618.83  5427.4 1619.94
#Mann=3,-1,0
  4573.0    0.05       0  5011.5    0.05       0  5015.7    0.05       0
Bank Sta=5011.5,5015.7
Exp/Cntr=0.3,0.1

Type RM Length L Ch R = 1,10912,294,294,294
BEGIN DESCRIPTION:
Deadman 04 21.0
END DESCRIPTION:
XS GIS Cut Line= 3
      1614454.97      6932188.03      1614705.00      6931938.00
      1614955.04      6931687.96
#Sta/Elev= 30
  4641.8 1608.92  4656.0 1608.00  4684.3 1602.57  4740.8 1594.44  4825.7 1592.76
  4854.0 1591.41  4868.1 1590.30  4896.4 1589.68  4924.7 1588.13  4967.1 1587.54
  4981.3 1586.42  4989.8 1584.41  4990.0 1583.91  4993.7 1583.91  4994.0 1584.41
  5009.5 1584.61  5023.7 1585.60  5037.8 1587.19  5052.0 1587.79  5066.1 1589.47
  5080.2 1590.34  5193.4 1591.47  5221.7 1591.17  5235.8 1593.57  5250.0 1595.00
  5278.2 1600.03  5306.5 1609.77  5320.7 1612.48  5334.8 1614.37  5349.0 1614.96
#Mann=3,-1,0
  4641.8    0.05       0  4989.8    0.05       0  4994.0    0.05       0
Bank Sta=4989.8,4994
Exp/Cntr=0.3,0.1

Type RM Length L Ch R = 1,10618,177,177,177
BEGIN DESCRIPTION:
Mapping XS 7f10b90d
END DESCRIPTION:
XS GIS Cut Line= 3
      1614533.09      6932226.43      1614717.87      6932191.67
      1615144.29      6932147.74
#Sta/Elev= 30
  4673.7 1597.76  4677.2 1597.76  4685.8 1596.14  4691.6 1594.40  4736.7 1591.98
  4744.1 1591.14  4757.0 1590.71  4801.6 1591.07  4854.1 1589.22  4868.9 1589.20
  4979.5 1583.81  4997.3 1583.58  4997.7 1583.08  5001.5 1583.08  5001.8 1583.58
  5029.7 1585.43  5044.4 1585.28  5080.0 1586.14  5100.1 1588.97  5120.2 1590.54
  5150.4 1591.88  5180.5 1592.54  5190.6 1592.21  5200.6 1590.88  5210.7 1592.57
  5220.7 1593.32  5237.5 1593.64  5242.5 1594.19  5271.0 1594.06  5290.4 1594.54
#Mann=3,-1,0
  4673.7    0.05       0  4997.3    0.03       0  5001.8    0.05       0
Bank Sta=4997.3,5001.8
Exp/Cntr=0.3,0.1

Type RM Length L Ch R = 1,10441,430,430,430
BEGIN DESCRIPTION:
Deadman 04 20.0
END DESCRIPTION:
XS GIS Cut Line= 3
      1614505.04      6932338.00      1614809.37      6932323.42
      1615354.99      6932388.00
#Sta/Elev= 30
  4698.3 1608.55  4718.3 1605.31  4748.3 1599.24  4808.4 1591.54  4878.5 1589.79
  4928.5 1587.74  4998.3 1582.98  5028.8 1583.72  5036.6 1582.57  5037.0 1582.07
  5040.8 1582.07  5041.1 1582.57  5048.9 1584.12  5059.0 1584.28  5069.1 1582.77
  5084.3 1584.85  5099.3 1584.86  5119.4 1587.90  5230.2 1591.45  5300.7 1593.23
  5320.8 1591.95  5401.4 1592.40  5425.7 1594.96  5481.9 1602.81  5502.1 1607.34
  5508.5 1610.13  5513.5 1610.50  5522.2 1613.28  5532.3 1614.22  5552.4 1614.68
#Mann=3,-1,0
  4698.3    0.05       0  5036.6    0.05       0  5041.1    0.05       0
Bank Sta=5036.6,5041.1
Exp/Cntr=0.3,0.1

Type RM Length L Ch R = 1,10011,443,443,443
BEGIN DESCRIPTION:
Deadman 04 19.0
END DESCRIPTION:
XS GIS Cut Line= 3
      1614555.02      6932887.99      1614855.00      6932738.00
      1615255.01      6932437.99
#Sta/Elev= 30
  4665.1 1606.66  4667.9 1606.66  4673.5 1604.02  4679.1 1604.63  4695.8 1598.53
  4701.4 1599.27  4718.2 1593.61  4732.2 1593.17  4740.5 1590.35  4746.1 1590.31
  4754.5 1587.47  4785.3 1585.97  4844.0 1584.76  4857.9 1585.21  4911.0 1583.48
  4933.4 1583.53  4955.8 1584.83  4984.2 1578.99  4984.6 1578.49  4988.8 1578.99
  5014.0 1581.27  5128.6 1584.77  5136.9 1584.30  5200.5 1587.87  5300.5 1590.58
  5372.4 1593.71  5400.5 1594.30  5407.8 1593.45  5464.0 1594.80  5500.5 1598.73
#Mann=3,-1,0
  4665.1    0.05       0  4984.2    0.03       0  4988.8    0.05       0
Bank Sta=4984.2,4988.8
Exp/Cntr=0.3,0.1

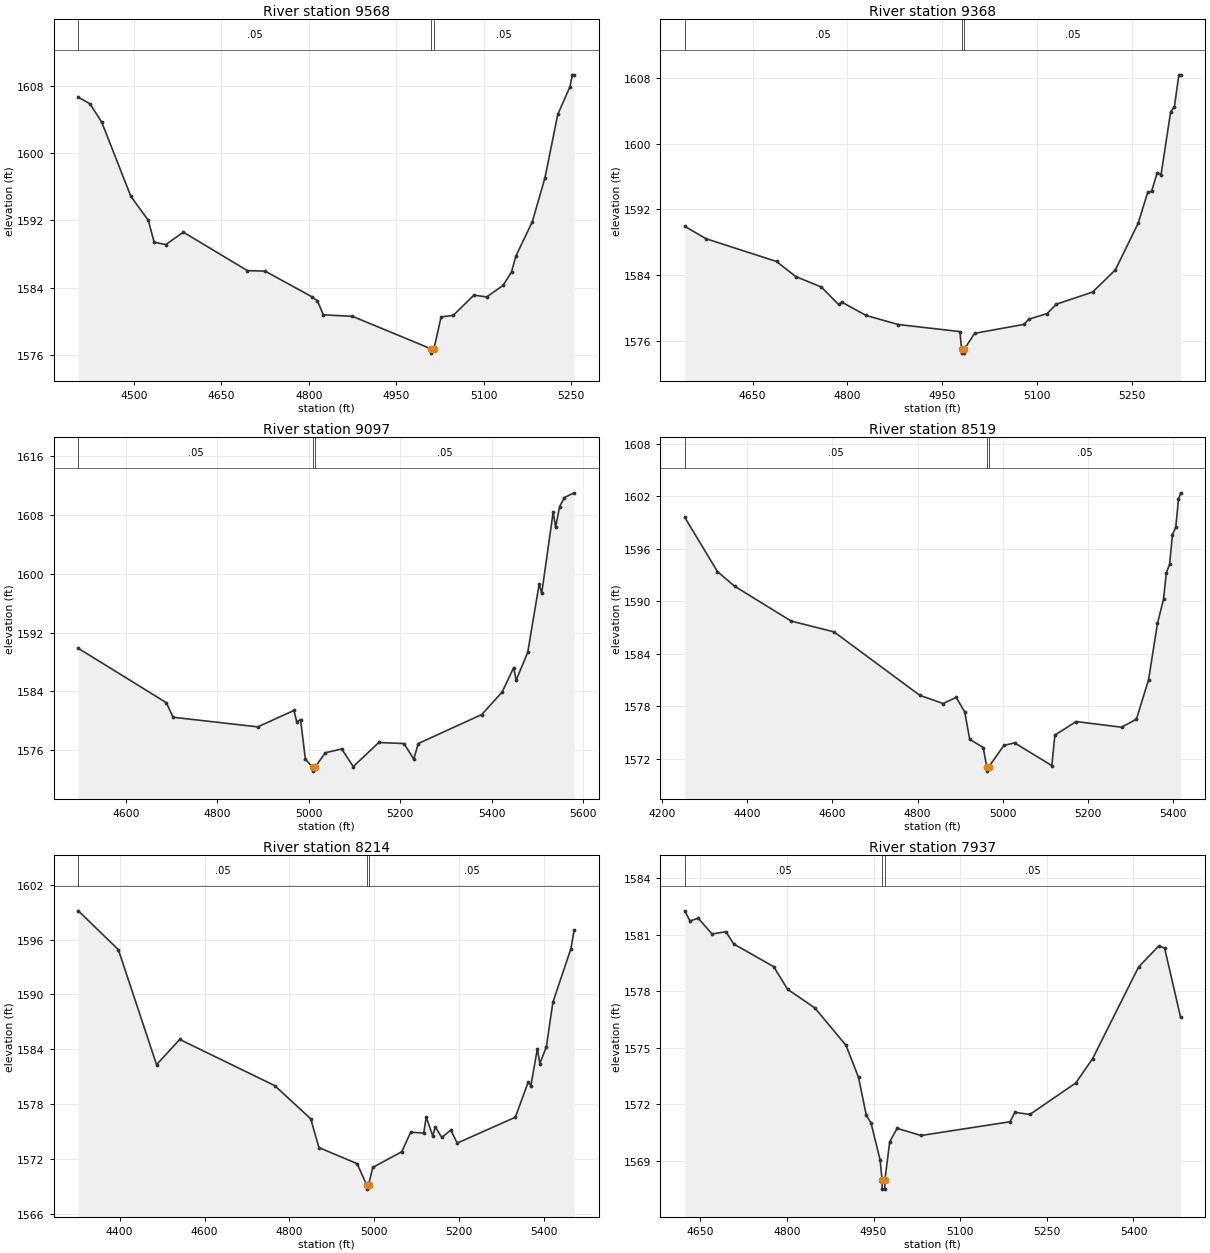
Type RM Length L Ch R = 1,9568,200,200,200
BEGIN DESCRIPTION:
Deadman 04 18.0
END DESCRIPTION:
XS GIS Cut Line= 3
      1614554.97      6933038.00      1615155.00      6933038.00
      1615354.97      6932888.02
#Sta/Elev= 30
  4404.9 1606.62  4424.9 1605.84  4444.9 1603.68  4494.9 1594.86  4524.9 1592.00
  4534.9 1589.40  4554.9 1589.13  4584.9 1590.60  4694.9 1586.03  4724.9 1585.98
  4804.9 1582.95  4814.9 1582.44  4824.9 1580.79  4874.9 1580.61  5009.9 1576.74
  5010.3 1576.24  5014.5 1576.74  5026.8 1580.54  5047.6 1580.72  5083.1 1583.13
  5104.9 1582.91  5133.1 1584.28  5147.6 1585.89  5154.9 1587.75  5183.1 1591.83
  5204.9 1597.07  5226.8 1604.58  5247.6 1607.85  5251.8 1609.28  5254.9 1609.28
#Mann=3,-1,0
  4404.9    0.05       0  5009.9    0.03       0  5014.5    0.05       0
Bank Sta=5009.9,5014.5
Exp/Cntr=0.3,0.1

Type RM Length L Ch R = 1,9368,271,271,271
BEGIN DESCRIPTION:
Mapping XS b0cda5dd
END DESCRIPTION:
XS GIS Cut Line= 3
      1614781.90      6933291.47      1615219.28      6933221.93
      1615407.75      6932938.31
#Sta/Elev= 30
  4543.0 1589.94  4576.5 1588.43  4687.9 1585.66  4718.3 1583.83  4758.8 1582.55
  4786.0 1580.43  4791.1 1580.71  4829.7 1579.09  4880.3 1577.99  4977.8 1577.13
  4980.2 1575.01  4980.5 1574.51  4984.4 1574.51  4984.8 1575.01  5000.9 1576.92
  5079.1 1578.01  5086.6 1578.64  5115.2 1579.31  5130.2 1580.47  5187.3 1581.94
  5223.4 1584.65  5259.5 1590.35  5274.5 1594.11  5280.5 1594.19  5289.5 1596.48
  5295.5 1596.23  5310.6 1603.86  5316.6 1604.50  5323.6 1608.37  5326.4 1608.37
#Mann=3,-1,0
  4543.0    0.05       0  4980.2    0.03       0  4984.8    0.05       0
Bank Sta=4980.2,4984.8
Exp/Cntr=0.3,0.1

Type RM Length L Ch R = 1,9097,578,578,578
BEGIN DESCRIPTION:
Deadman 04 17.0
END DESCRIPTION:
XS GIS Cut Line= 3
      1614855.02      6933737.99      1615255.00      6933438.00
      1615455.00      6932888.01
#Sta/Elev= 30
  4495.6 1589.86  4688.3 1582.45  4702.9 1580.47  4888.3 1579.16  4967.5 1581.40
  4973.7 1579.84  4982.0 1580.16  4992.5 1574.77  5008.5 1573.63  5008.9 1573.13
  5013.2 1573.63  5036.1 1575.63  5072.1 1576.15  5097.3 1573.75  5153.2 1577.03
  5208.4 1576.89  5229.7 1574.77  5239.6 1576.89  5378.6 1580.84  5423.2 1583.91
  5448.5 1587.24  5453.8 1585.52  5479.1 1589.30  5504.3 1598.64  5509.7 1597.33
  5534.9 1608.44  5540.2 1606.36  5548.9 1609.15  5559.5 1610.40  5580.8 1611.04
#Mann=3,-1,0
  4495.6    0.05       0  5008.5    0.03       0  5013.2    0.05       0
Bank Sta=5008.5,5013.2
Exp/Cntr=0.3,0.1

Type RM Length L Ch R = 1,8519,305,305,305
BEGIN DESCRIPTION:
Deadman 04 16.0
END DESCRIPTION:
XS GIS Cut Line= 3
      1614805.02      6933987.99      1615578.23      6933708.79
      1615841.07      6933487.45
#Sta/Elev= 30
  4252.8 1599.60  4329.5 1593.41  4369.7 1591.74  4502.8 1587.75  4603.6 1586.51
  4805.6 1579.25  4860.2 1578.32  4890.9 1579.02  4911.0 1577.35  4922.6 1574.23
  4954.5 1573.29  4962.6 1571.09  4963.0 1570.59  4967.6 1571.09  5003.0 1573.53
  5028.3 1573.82  5115.7 1571.22  5122.9 1574.71  5172.9 1576.26  5279.5 1575.61
  5314.6 1576.53  5343.2 1581.06  5364.1 1587.49  5378.4 1590.27  5384.9 1593.26
  5392.7 1594.28  5399.2 1597.62  5407.0 1598.46  5413.5 1601.67  5418.5 1602.41
#Mann=3,-1,0
  4252.8    0.05       0  4962.6    0.03       0  4967.6    0.05       0
Bank Sta=4962.6,4967.6
Exp/Cntr=0.3,0.1

Type RM Length L Ch R = 1,8214,277,277,277
BEGIN DESCRIPTION:
Deadman 04 15.0
END DESCRIPTION:
XS GIS Cut Line= 3
      1615055.02      6934187.99      1615705.00      6933938.00
      1615955.00      6933537.99
#Sta/Elev= 30
  4302.7 1599.14  4397.0 1594.89  4487.0 1582.30  4541.6 1585.06  4765.5 1580.00
  4850.2 1576.37  4869.5 1573.22  4959.5 1571.46  4981.6 1569.17  4982.0 1568.67
  4986.6 1569.17  4996.4 1571.05  5064.5 1572.76  5085.8 1574.91  5116.4 1574.80
  5122.3 1576.56  5137.7 1574.50  5143.6 1575.49  5158.9 1574.33  5180.1 1575.13
  5195.4 1573.71  5332.2 1576.54  5362.9 1580.44  5368.8 1579.97  5384.1 1584.04
  5390.0 1582.41  5405.3 1584.25  5420.7 1589.14  5463.1 1594.99  5470.8 1597.05
#Mann=3,-1,0
  4302.7    0.05       0  4981.6    0.03       0  4986.6    0.05       0
Bank Sta=4981.6,4986.6
Exp/Cntr=0.3,0.1

Type RM Length L Ch R = 1,7937,211,211,211
BEGIN DESCRIPTION:
Mapping XS eb15afdd
END DESCRIPTION:
XS GIS Cut Line= 3
      1615376.64      6934351.02      1615832.31      6934164.36
      1615928.79      6933811.22
#Sta/Elev= 30
  4623.2 1582.28  4632.2 1581.74  4646.4 1581.89  4670.4 1581.05  4694.4 1581.17
  4707.9 1580.52  4777.2 1579.31  4801.2 1578.11  4848.4 1577.12  4902.4 1575.13
  4924.0 1573.43  4937.4 1571.42  4945.6 1571.01  4961.4 1569.04  4964.7 1567.99
  4965.1 1567.49  4969.4 1567.49  4969.7 1567.99  4978.0 1570.01  4990.8 1570.72
  5032.1 1570.34  5186.2 1571.07  5194.8 1571.57  5220.7 1571.46  5300.1 1573.13
  5329.4 1574.43  5408.8 1579.29  5443.4 1580.40  5453.9 1580.31  5481.7 1576.62
#Mann=3,-1,0
  4623.2    0.05       0  4964.7    0.03       0  4969.7    0.05       0
Bank Sta=4964.7,4969.7
Exp/Cntr=0.3,0.1

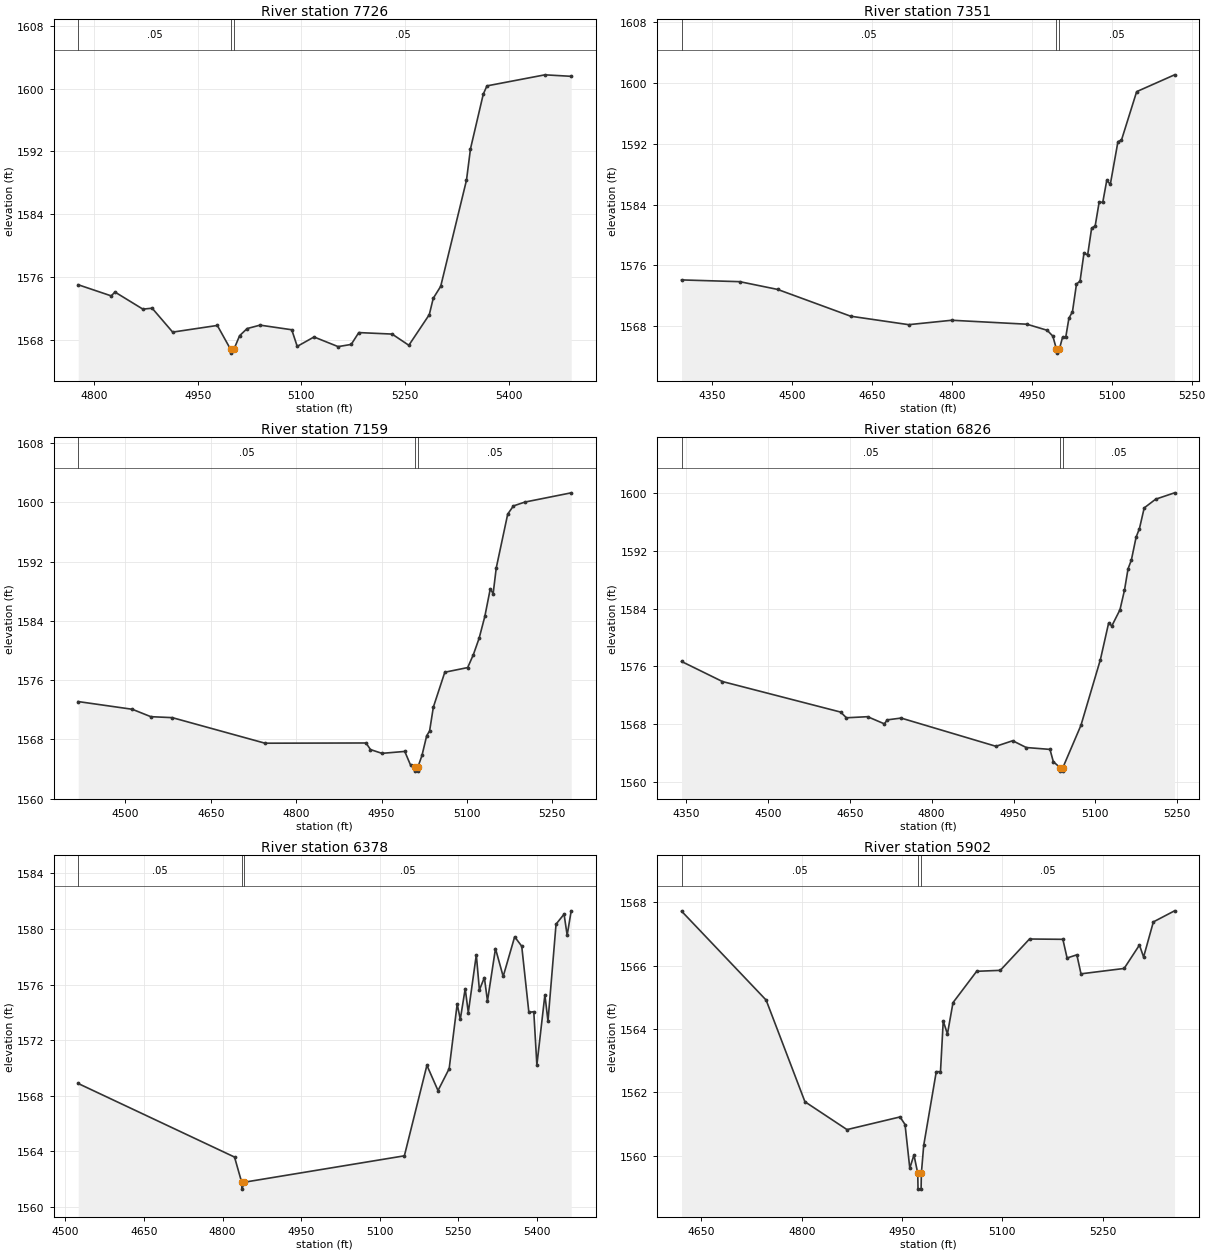
Type RM Length L Ch R = 1,7726,375,375,375
BEGIN DESCRIPTION:
Mapping XS c9ee6324
END DESCRIPTION:
XS GIS Cut Line= 2
      1615598.11      6934471.78      1616260.27      6934206.55
#Sta/Elev= 30
  4777.1 1574.99  4824.9 1573.57  4830.3 1574.06  4870.7 1571.88  4884.1 1572.00
  4913.8 1568.95  4978.4 1569.80  4997.5 1566.77  4997.8 1566.27  5002.5 1566.77
  5010.6 1568.49  5021.5 1569.40  5040.2 1569.84  5086.1 1569.25  5094.0 1567.13
  5118.3 1568.33  5153.2 1567.10  5172.1 1567.38  5183.1 1568.89  5231.3 1568.70
  5255.5 1567.27  5285.1 1571.18  5290.8 1573.26  5301.6 1574.79  5338.9 1588.32
  5344.7 1592.33  5363.2 1599.30  5368.5 1600.35  5452.4 1601.76  5490.4 1601.57
#Mann=3,-1,0
  4777.1    0.05       0  4997.5    0.03       0  5002.5    0.05       0
Bank Sta=4997.5,5002.5
Exp/Cntr=0.3,0.1

Type RM Length L Ch R = 1,7351,192,192,192
BEGIN DESCRIPTION:
Deadman 04 14.0
END DESCRIPTION:
XS GIS Cut Line= 3
      1615383.83      6934736.56      1616064.34      6934510.88
      1616219.76      6934372.72
#Sta/Elev= 30
  4292.9 1574.10  4402.1 1573.87  4473.2 1572.85  4610.2 1569.33  4719.0 1568.22
  4799.8 1568.80  4940.8 1568.28  4978.9 1567.48  4989.5 1566.71  4996.3 1564.98
  4996.7 1564.48  5001.6 1564.98  5007.6 1566.54  5013.6 1566.54  5019.6 1569.06
  5026.3 1569.93  5033.8 1573.55  5040.5 1573.95  5048.0 1577.68  5054.7 1577.35
  5062.2 1580.89  5068.9 1581.20  5076.4 1584.34  5083.1 1584.29  5090.6 1587.17
  5097.3 1586.67  5111.6 1592.27  5118.2 1592.47  5146.7 1598.84  5217.8 1601.05
#Mann=3,-1,0
  4292.9    0.05       0  4996.3    0.03       0  5001.6    0.05       0
Bank Sta=4996.3,5001.6
Exp/Cntr=0.3,0.1

Type RM Length L Ch R = 1,7159,333,333,333
BEGIN DESCRIPTION:
Mapping XS 675da53d
END DESCRIPTION:
XS GIS Cut Line= 3
      1615438.83      6934781.07      1615792.06      6934671.26
      1616286.11      6934715.17
#Sta/Elev= 30
  4417.2 1573.11  4512.2 1572.07  4544.8 1571.07  4582.5 1570.94  4745.3 1567.49
  4922.7 1567.52  4930.6 1566.63  4950.7 1566.12  4990.8 1566.38  5000.9 1564.54
  5008.3 1564.22  5008.7 1563.72  5013.2 1563.72  5013.6 1564.22  5021.0 1565.83
  5029.3 1568.50  5034.4 1569.14  5041.0 1572.36  5061.1 1577.07  5101.3 1577.70
  5111.3 1579.45  5121.4 1581.66  5131.4 1584.60  5141.0 1588.34  5146.0 1587.67
  5151.5 1591.16  5171.6 1598.42  5181.6 1599.52  5201.7 1600.04  5283.1 1601.29
#Mann=3,-1,0
  4417.2    0.05       0  5008.3    0.03       0  5013.6    0.05       0
Bank Sta=5008.3,5013.6
Exp/Cntr=0.3,0.1

Type RM Length L Ch R = 1,6826,448,448,448
BEGIN DESCRIPTION:
Deadman 04 13.0
END DESCRIPTION:
XS GIS Cut Line= 3
      1615390.77      6935208.78      1616005.00      6934988.00
      1616210.06      6934844.29
#Sta/Elev= 30
  4341.9 1576.67  4416.8 1573.89  4633.3 1569.66  4643.9 1568.87  4682.7 1569.02
  4713.4 1568.03  4718.7 1568.58  4744.1 1568.83  4917.8 1564.92  4948.5 1565.69
  4973.3 1564.75  5016.8 1564.49  5022.9 1562.79  5035.1 1561.98  5035.5 1561.48
  5040.0 1561.48  5040.5 1561.98  5073.5 1567.82  5109.2 1576.94  5124.1 1581.95
  5130.2 1581.61  5145.0 1583.83  5153.3 1586.55  5159.8 1589.50  5165.9 1590.72
  5174.6 1593.90  5180.7 1595.08  5189.4 1597.94  5210.4 1599.15  5245.0 1600.03
#Mann=3,-1,0
  4341.9    0.05       0  5035.1    0.03       0  5040.5    0.05       0
Bank Sta=5035.1,5040.5
Exp/Cntr=0.3,0.1

Type RM Length L Ch R = 1,6378,476,476,476
BEGIN DESCRIPTION:
Deadman 04 12.0
END DESCRIPTION:
XS GIS Cut Line= 3
      1615737.99      6935292.13      1616205.00      6935338.00
      1616455.03      6934937.96
#Sta/Elev= 30
  4524.4 1568.87  4822.8 1563.57  4836.4 1561.76  4836.8 1561.26  4841.8 1561.76
  5147.0 1563.66  5190.0 1570.18  5211.2 1568.36  5232.5 1569.94  5247.8 1574.60
  5253.7 1573.49  5263.1 1575.70  5269.0 1573.98  5284.3 1578.14  5290.2 1575.61
  5299.7 1576.50  5305.6 1574.81  5320.9 1578.59  5335.6 1576.58  5357.5 1579.44
  5371.0 1578.76  5384.6 1574.00  5394.0 1574.04  5399.9 1570.20  5415.2 1575.26
  5421.1 1573.36  5436.5 1580.35  5451.8 1581.07  5457.7 1579.55  5465.4 1581.31
#Mann=3,-1,0
  4524.4    0.05       0  4836.4    0.03       0  4841.8    0.05       0
Bank Sta=4836.4,4841.8
Exp/Cntr=0.3,0.1

Type RM Length L Ch R = 1,5902,478,478,478
BEGIN DESCRIPTION:
Deadman 04 11.0
END DESCRIPTION:
XS GIS Cut Line= 3
      1615775.57      6935330.02      1616005.00      6935638.00
      1616286.58      6935851.16
#Sta/Elev= 30
  4620.2 1567.72  4746.7 1564.91  4804.7 1561.70  4867.6 1560.82  4946.9 1561.22
  4954.4 1560.98  4961.5 1559.60  4967.7 1560.02  4973.4 1559.44  4973.8 1558.94
  4978.4 1558.94  4978.8 1559.44  4982.3 1560.32  5001.1 1562.65  5007.4 1562.65
  5011.5 1564.25  5017.8 1563.84  5026.1 1564.83  5061.5 1565.82  5096.8 1565.85
  5140.5 1566.84  5190.4 1566.83  5196.7 1566.24  5211.3 1566.34  5217.5 1565.74
  5282.0 1565.91  5304.9 1566.65  5311.1 1566.27  5325.7 1567.38  5357.4 1567.73
#Mann=3,-1,0
  4620.2    0.05       0  4973.4    0.03       0  4978.8    0.05       0
Bank Sta=4973.4,4978.8
Exp/Cntr=0.3,0.1

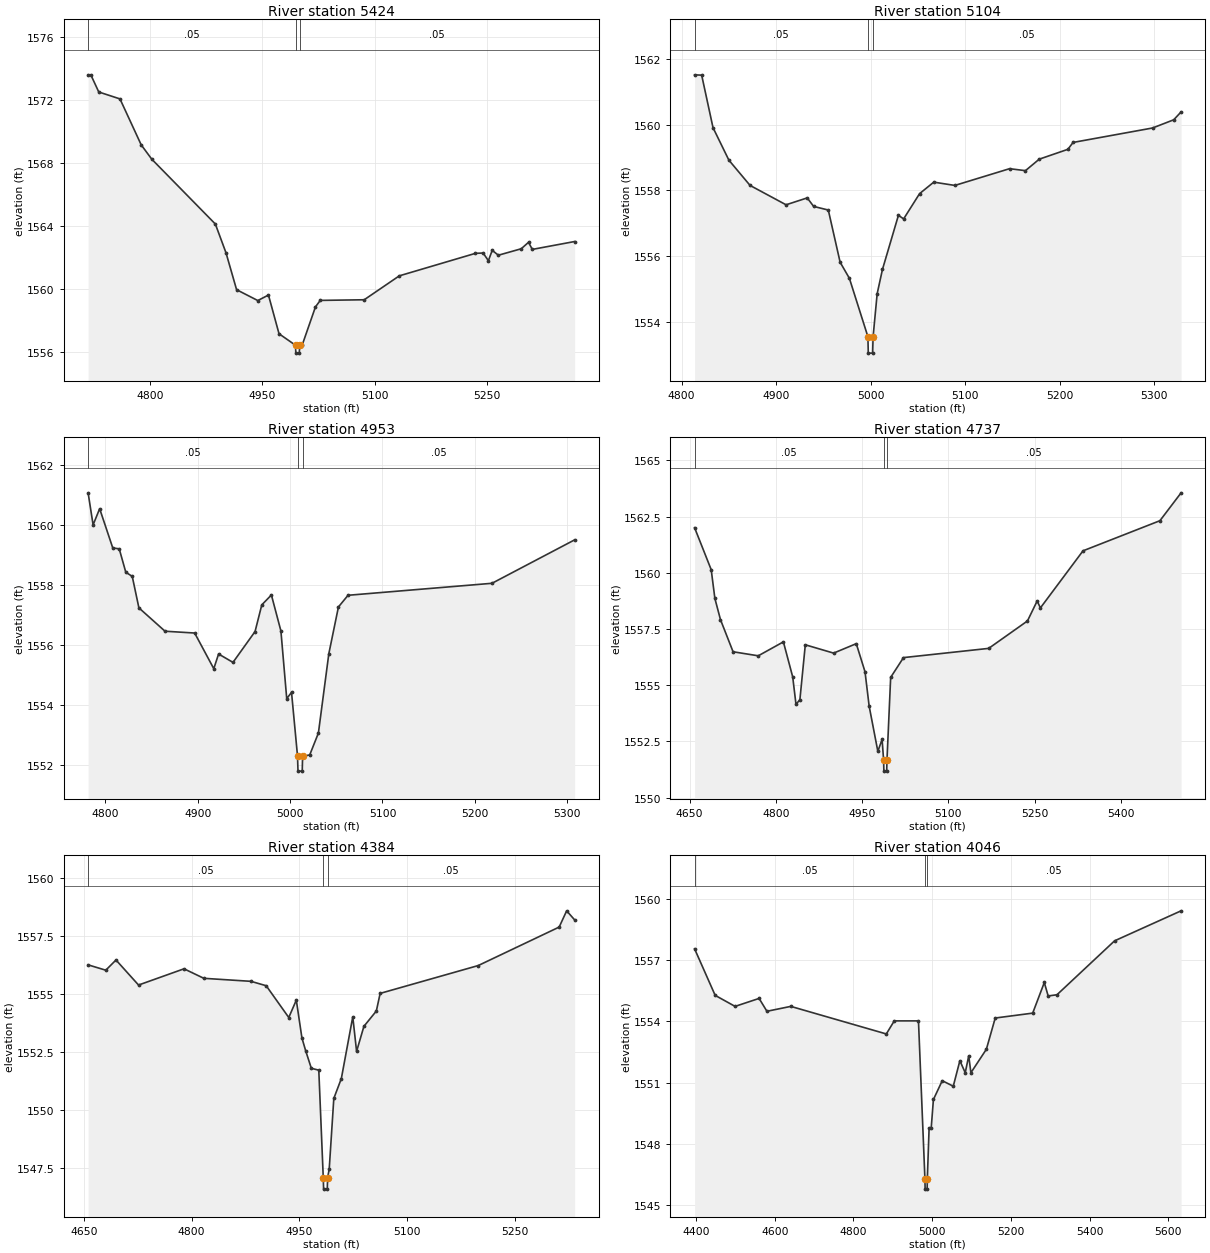
Type RM Length L Ch R = 1,5424,320,320,320
BEGIN DESCRIPTION:
Deadman 04 10.0
END DESCRIPTION:
XS GIS Cut Line= 3
      1615454.97      6935637.97      1615655.00      6935838.00
      1616015.07      6935903.12
#Sta/Elev= 30
  4717.7 1573.58  4721.3 1573.58  4731.9 1572.49  4760.2 1572.05  4788.5 1569.13
  4802.6 1568.22  4887.4 1564.10  4901.6 1562.27  4915.7 1559.93  4944.0 1559.24
  4958.2 1559.59  4972.3 1557.13  4994.3 1556.40  4994.7 1555.90  4999.3 1555.90
  4999.8 1556.40  5003.1 1556.40  5020.9 1558.84  5027.3 1559.25  5085.9 1559.29
  5132.7 1560.81  5234.3 1562.24  5244.5 1562.26  5251.5 1561.77  5256.6 1562.43
  5264.8 1562.12  5295.3 1562.53  5305.0 1562.94  5310.1 1562.49  5366.5 1562.99
#Mann=3,-1,0
  4717.7    0.05       0  4994.3    0.03       0  4999.8    0.05       0
Bank Sta=4994.3,4999.8
Exp/Cntr=0.3,0.1

Type RM Length L Ch R = 1,5104,151,151,151
BEGIN DESCRIPTION:
Mapping XS 541221c7
END DESCRIPTION:
XS GIS Cut Line= 2
      1615488.25      6936239.54      1615949.43      6936010.78
#Sta/Elev= 30
  4813.8 1561.52  4821.3 1561.51  4833.3 1559.91  4850.1 1558.92  4872.5 1558.15
  4910.6 1557.56  4933.0 1557.77  4939.8 1557.51  4955.3 1557.40  4967.8 1555.81
  4977.6 1555.32  4997.2 1553.54  4997.6 1553.04  5002.2 1553.04  5002.7 1553.54
  5007.0 1554.85  5012.6 1555.59  5029.5 1557.24  5035.0 1557.13  5051.9 1557.90
  5066.9 1558.25  5089.2 1558.15  5147.1 1558.66  5163.9 1558.60  5178.5 1558.95
  5208.8 1559.25  5214.3 1559.46  5298.4 1559.90  5320.8 1560.15  5328.6 1560.39
#Mann=3,-1,0
  4813.8    0.05       0  4997.2    0.03       0  5002.7    0.05       0
Bank Sta=4997.2,5002.7
Exp/Cntr=0.3,0.1

Type RM Length L Ch R = 1,4953,216,216,216
BEGIN DESCRIPTION:
Mapping XS 5f978f18
END DESCRIPTION:
XS GIS Cut Line= 4
      1615519.37      6936255.97      1615586.58      6936324.97
      1615782.91      6936270.64      1615885.24      6936068.17
#Sta/Elev= 30
  4781.2 1561.07  4786.6 1560.00  4793.7 1560.54  4807.9 1559.23  4814.9 1559.20
  4822.0 1558.42  4829.0 1558.28  4836.2 1557.23  4864.5 1556.45  4896.6 1556.39
  4917.3 1555.20  4922.5 1555.69  4938.1 1555.41  4962.0 1556.44  4969.3 1557.33
  4979.7 1557.66  4990.0 1556.46  4996.3 1554.20  5001.5 1554.41  5008.0 1552.28
  5008.5 1551.78  5013.1 1551.78  5013.5 1552.28  5021.2 1552.32  5030.6 1553.05
  5041.9 1555.70  5052.3 1557.26  5062.7 1557.65  5218.6 1558.05  5308.1 1559.50
#Mann=3,-1,0
  4781.2    0.05       0  5008.0    0.05       0  5013.5    0.05       0
Bank Sta=5008,5013.5
Exp/Cntr=0.3,0.1

Type RM Length L Ch R = 1,4737,353,353,353
BEGIN DESCRIPTION:
Mapping XS 4de8f960
END DESCRIPTION:
XS GIS Cut Line= 3
      1615496.64      6936256.94      1615606.65      6936460.35
      1616158.01      6936731.77
#Sta/Elev= 30
  4658.8 1562.01  4687.7 1560.14  4694.1 1558.86  4703.8 1557.92  4725.7 1556.49
  4769.5 1556.31  4813.2 1556.93  4829.4 1555.37  4835.1 1554.15  4841.9 1554.36
  4851.3 1556.80  4900.5 1556.43  4939.9 1556.85  4955.1 1555.60  4962.3 1554.07
  4977.4 1552.06  4984.8 1552.59  4987.4 1551.68  4987.9 1551.18  4992.8 1551.18
  4993.3 1551.68  4999.7 1555.35  5022.0 1556.23  5170.1 1556.64  5237.5 1557.86
  5254.4 1558.75  5260.0 1558.44  5334.1 1560.98  5467.8 1562.32  5504.6 1563.56
#Mann=3,-1,0
  4658.8    0.05       0  4987.4    0.05       0  4993.3    0.05       0
Bank Sta=4987.4,4993.3
Exp/Cntr=0.3,0.1

Type RM Length L Ch R = 1,4384,338,338,338
BEGIN DESCRIPTION:
Mapping XS e3ce03f2
END DESCRIPTION:
XS GIS Cut Line= 2
      1615422.41      6936440.85      1615620.03      6937088.58
#Sta/Elev= 30
  4656.0 1556.27  4680.6 1556.04  4694.8 1556.48  4726.2 1555.40  4789.5 1556.10
  4817.1 1555.69  4882.7 1555.56  4903.9 1555.37  4935.3 1554.00  4945.8 1554.75
  4953.6 1553.12  4958.8 1552.57  4966.7 1551.81  4977.1 1551.73  4983.3 1547.10
  4983.8 1546.60  4988.9 1546.60  4989.4 1547.10  4991.6 1547.46  4998.0 1550.51
  5008.5 1551.37  5024.4 1554.03  5029.7 1552.54  5039.9 1553.62  5057.2 1554.28
  5062.5 1555.04  5199.0 1556.24  5311.7 1557.90  5322.1 1558.60  5333.2 1558.21
#Mann=3,-1,0
  4656.0    0.05       0  4983.3    0.05       0  4989.4    0.05       0
Bank Sta=4983.3,4989.4
Exp/Cntr=0.3,0.1

Type RM Length L Ch R = 1,4046,381,381,381
BEGIN DESCRIPTION:
Deadman 04 9.0
END DESCRIPTION:
XS GIS Cut Line= 3
      1615116.42      6936146.26      1615205.00      6936738.00
      1615487.94      6937309.45
#Sta/Elev= 30
  4396.3 1557.56  4448.6 1555.28  4499.2 1554.74  4560.2 1555.13  4580.1 1554.50
  4640.7 1554.74  4883.4 1553.39  4903.6 1554.03  4965.1 1554.03  4981.5 1546.29
  4982.0 1545.79  4987.1 1545.79  4987.6 1546.29  4992.1 1548.77  4997.4 1548.77
  5003.1 1550.18  5025.5 1551.10  5053.5 1550.83  5070.3 1552.08  5083.9 1551.49
  5092.8 1552.32  5098.3 1551.49  5137.6 1552.64  5160.1 1554.17  5255.3 1554.41
  5284.8 1555.91  5294.6 1555.25  5317.0 1555.31  5463.3 1557.95  5632.3 1559.42
#Mann=3,-1,0
  4396.3    0.05       0  4981.5    0.05       0  4987.6    0.05       0
Bank Sta=4981.5,4987.6
Exp/Cntr=0.3,0.1