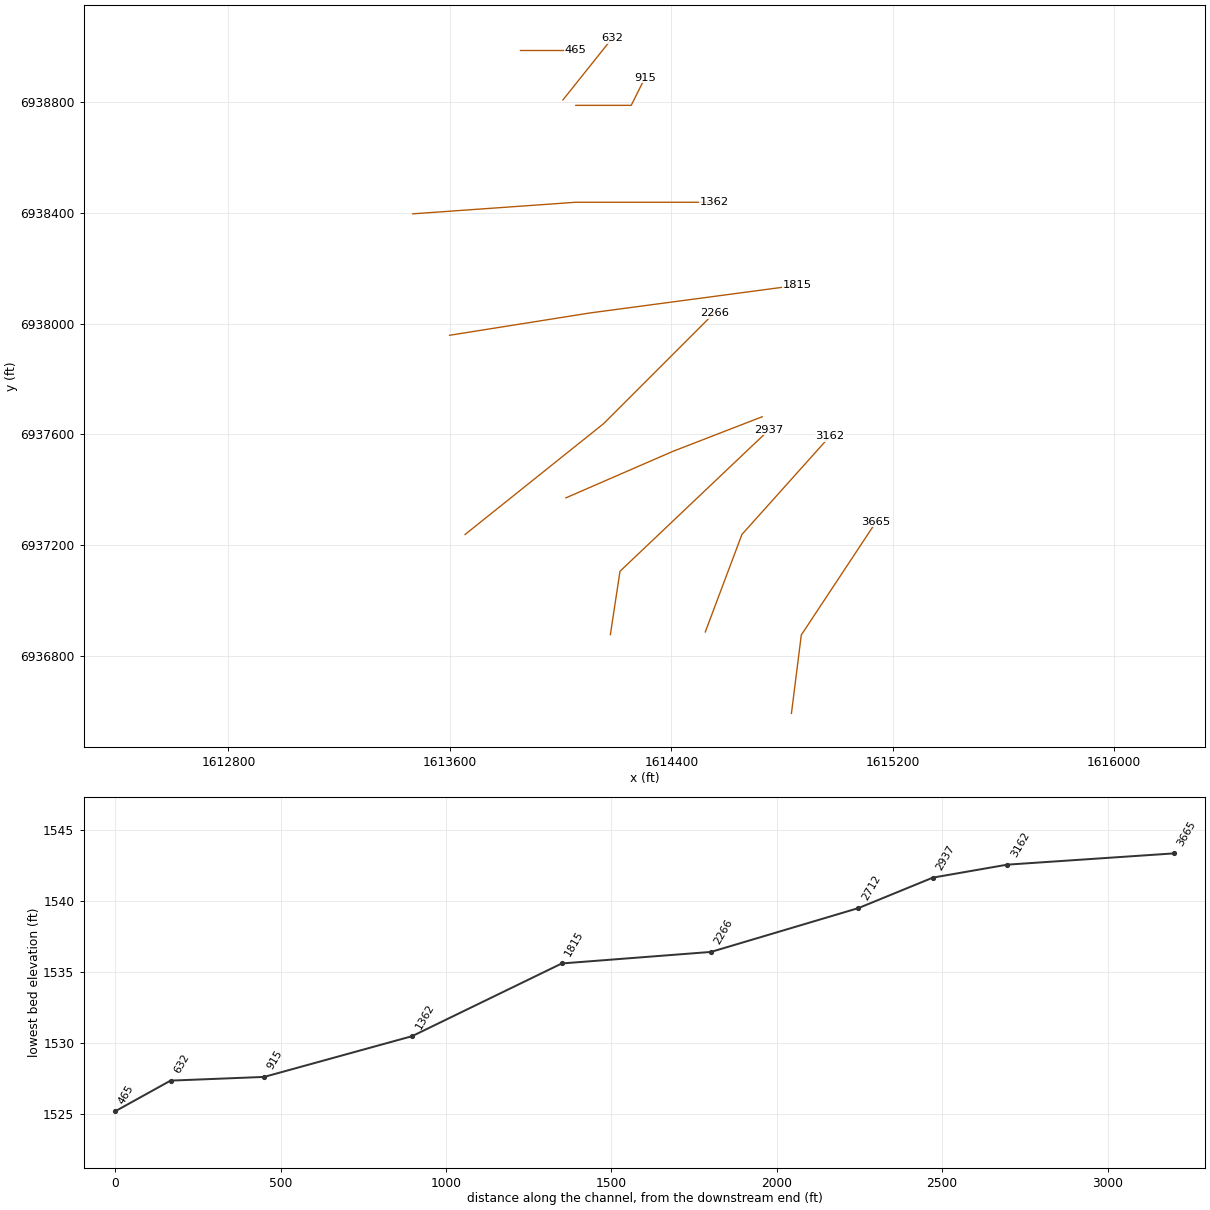
HEC-RAS study Deadman 04.prj: Deadman 04 Base Level Engineering

--- Deadman 04.g01 (geometry) --- (continued)

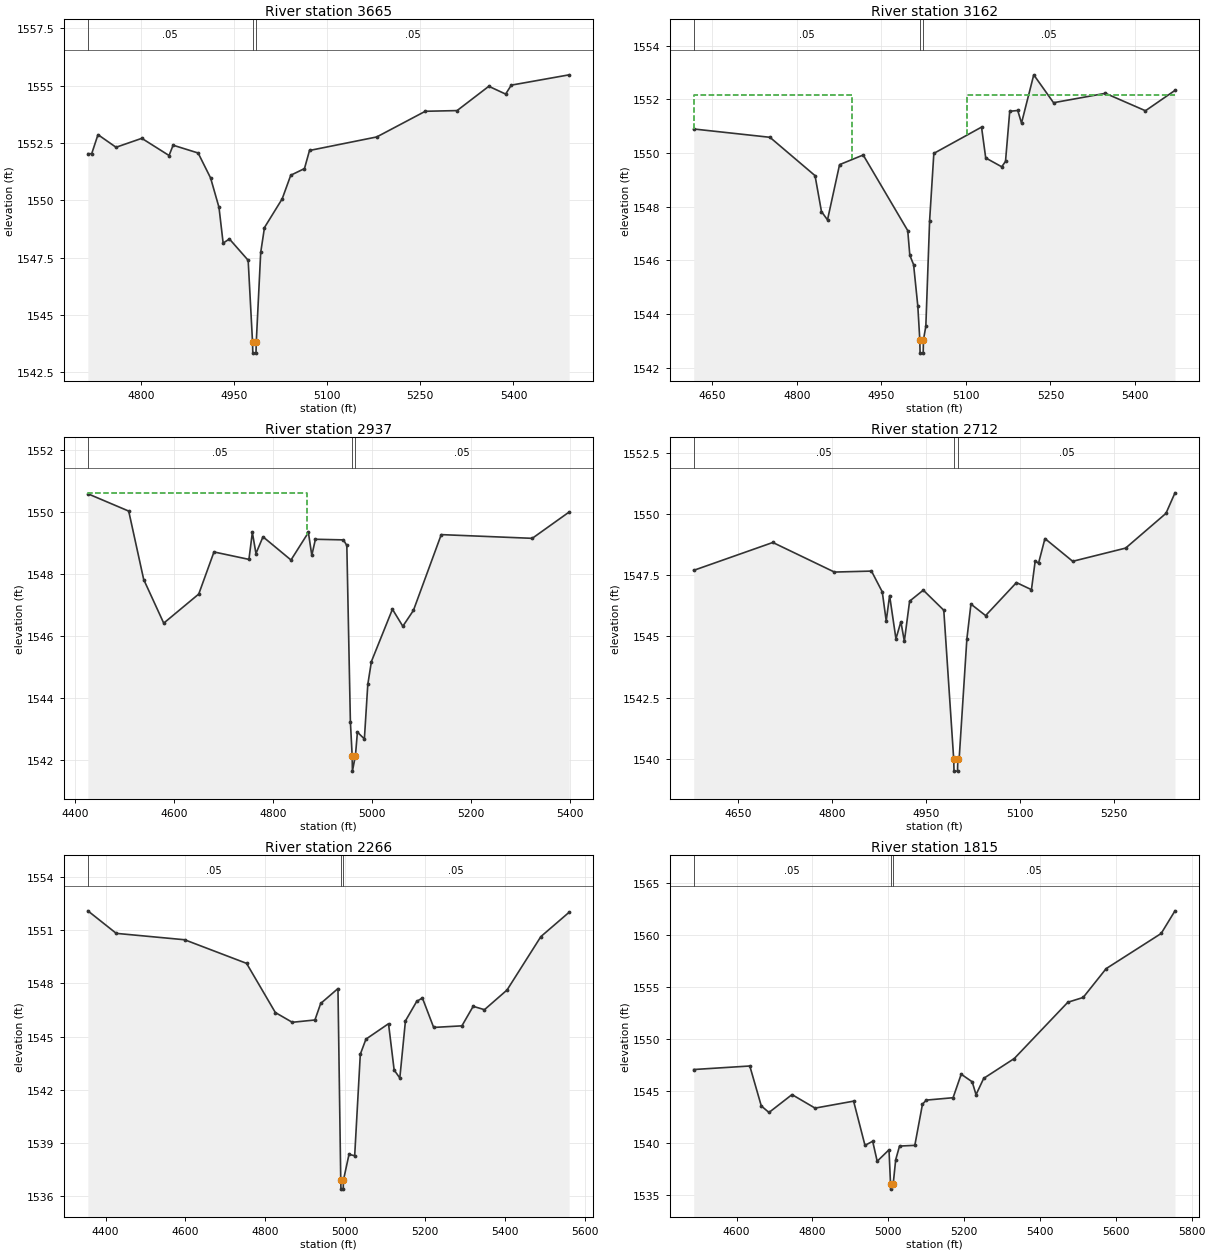
Type RM Length L Ch R = 1,3665,503,503,503
BEGIN DESCRIPTION:
Deadman 04 8.0
END DESCRIPTION:
XS GIS Cut Line= 3
      1614833.85      6936591.81      1614869.47      6936875.08
      1615139.63      6937283.52
#Sta/Elev= 30
  4714.5 1552.03  4720.7 1552.03  4730.8 1552.86  4759.9 1552.31  4801.4 1552.70
  4845.3 1551.95  4851.8 1552.40  4892.1 1552.06  4912.2 1550.97  4925.7 1549.69
  4932.4 1548.13  4942.5 1548.31  4972.7 1547.38  4979.7 1543.83  4980.2 1543.33
  4985.3 1543.33  4985.8 1543.83  4992.9 1547.72  4999.0 1548.81  5027.5 1550.06
  5041.3 1551.09  5063.4 1551.38  5071.5 1552.17  5179.8 1552.76  5258.0 1553.88
  5309.2 1553.91  5360.3 1554.97  5387.4 1554.63  5396.5 1555.02  5489.7 1555.47
#Mann=3,-1,0
  4714.5    0.05       0  4979.7    0.05       0  4985.8    0.05       0
Bank Sta=4979.7,4985.8
Exp/Cntr=0.3,0.1

Type RM Length L Ch R = 1,3162,225,225,225
BEGIN DESCRIPTION:
Deadman 04 7.0
END DESCRIPTION:
XS GIS Cut Line= 3
      1614522.66      6936885.84      1614655.00      6937238.00
      1614973.52      6937593.60
#Sta/Elev= 30
  4617.3 1550.90  4752.5 1550.59  4832.5 1549.16  4843.9 1547.82  4854.6 1547.51
  4876.0 1549.57  4917.9 1549.93  4996.9 1547.11  5000.6 1546.19  5007.3 1545.84
  5014.8 1544.29  5018.3 1543.04  5018.8 1542.54  5024.3 1542.54  5024.8 1543.04
  5029.0 1543.54  5035.7 1547.48  5043.2 1549.99  5127.8 1550.97  5135.2 1549.82
  5163.6 1549.49  5170.3 1549.69  5177.8 1551.56  5192.0 1551.59  5198.7 1551.12
  5220.4 1552.92  5255.5 1551.88  5347.5 1552.23  5418.5 1551.58  5470.9 1552.34
#Mann=3,-1,0
  4617.3    0.05       0  5018.3    0.03       0  5024.8    0.05       0
#XS Ineff=2,0
    0.00 4898.50 1552.16 5101.50    0.00 1552.16
Permanent Ineff=
       F       F
Bank Sta=5018.3,5024.8
Exp/Cntr=0.3,0.1

Type RM Length L Ch R = 1,2937,225,225,225
BEGIN DESCRIPTION:
Mapping XS 22579664
END DESCRIPTION:
XS GIS Cut Line= 3
      1614179.87      6936876.36      1614214.63      6937105.10
      1614752.66      6937615.68
#Sta/Elev= 30
  4425.2 1550.59  4507.8 1550.03  4538.1 1547.82  4578.6 1546.41  4649.4 1547.35
  4680.2 1548.71  4750.9 1548.47  4757.8 1549.34  4765.1 1548.66  4779.3 1549.20
  4835.9 1548.45  4871.1 1549.34  4878.0 1548.60  4885.3 1549.12  4941.9 1549.10
  4948.8 1548.92  4956.0 1543.22  4959.6 1542.13  4960.1 1541.63  4966.2 1542.13
  4970.2 1542.89  4984.3 1542.67  4991.2 1544.43  4998.5 1545.17  5041.0 1546.86
  5062.0 1546.31  5083.4 1546.82  5139.7 1549.27  5323.7 1549.15  5398.3 1550.00
#Mann=3,-1,0
  4425.2    0.05       0  4959.6    0.05       0  4966.2    0.05       0
#XS Ineff=2,0
    0.00 4868.10 1550.62               0
Permanent Ineff=
       F       F
Bank Sta=4959.6,4966.2
Exp/Cntr=0.3,0.1

Type RM Length L Ch R = 1,2712,446,446,446
BEGIN DESCRIPTION:
Deadman 04 6.0
END DESCRIPTION:
XS GIS Cut Line= 3
      1614019.25      6937370.27      1614405.00      6937538.00
      1614728.43      6937663.33
#Sta/Elev= 30
  4579.6 1547.70  4705.8 1548.84  4804.0 1547.63  4863.1 1547.67  4880.3 1546.82
  4886.6 1545.63  4892.0 1546.67  4902.1 1544.90  4910.0 1545.60  4915.5 1544.80
  4923.9 1546.44  4945.7 1546.89  4978.4 1546.07  4994.2 1539.99  4994.7 1539.49
  5000.3 1539.49  5000.8 1539.99  5002.9 1539.99  5015.2 1544.89  5021.7 1546.32
  5045.1 1545.85  5094.3 1547.20  5118.2 1546.91  5124.2 1548.09  5129.5 1547.99
  5139.7 1549.00  5184.0 1548.07  5268.4 1548.61  5332.7 1550.03  5347.1 1550.87
#Mann=3,-1,0
  4579.6    0.05       0  4994.2    0.05       0  5000.8    0.05       0
Bank Sta=4994.2,5000.8
Exp/Cntr=0.3,0.1

Type RM Length L Ch R = 1,2266,451,451,451
BEGIN DESCRIPTION:
Deadman 04 5.0
END DESCRIPTION:
XS GIS Cut Line= 3
      1613655.03      6937238.03      1614155.00      6937638.00
      1614555.03      6938038.03
#Sta/Elev= 30
  4355.4 1552.09  4426.6 1550.82  4597.9 1550.46  4753.1 1549.13  4825.2 1546.36
  4867.6 1545.81  4924.4 1545.94  4938.8 1546.87  4982.1 1547.71  4989.1 1536.91
  4989.6 1536.41  4995.3 1536.41  4995.8 1536.91  5009.8 1538.37  5024.0 1538.29
  5038.1 1544.01  5052.2 1544.86  5108.8 1545.73  5122.9 1543.12  5137.1 1542.67
  5151.2 1545.89  5179.5 1546.99  5193.7 1547.18  5221.9 1545.52  5292.7 1545.61
  5320.9 1546.71  5349.2 1546.52  5405.8 1547.63  5490.6 1550.64  5561.4 1552.01
#Mann=3,-1,0
  4355.4    0.05       0  4989.1    0.05       0  4995.8    0.05       0
Bank Sta=4989.1,4995.8
Exp/Cntr=0.3,0.1

Type RM Length L Ch R = 1,1815,453,453,453
BEGIN DESCRIPTION:
Deadman 04 4.0
END DESCRIPTION:
XS GIS Cut Line= 3
      1613598.97      6937957.52      1614105.00      6938038.00
      1614854.97      6938138.00
#Sta/Elev= 30
  4487.1 1547.10  4635.0 1547.44  4665.3 1543.60  4685.6 1542.97  4746.3 1544.69
  4807.1 1543.39  4908.7 1544.06  4938.7 1539.81  4959.0 1540.20  4970.9 1538.28
  5002.0 1539.38  5006.1 1536.10  5006.6 1535.60  5013.1 1536.10  5019.7 1538.43
  5029.8 1539.74  5070.1 1539.81  5090.3 1543.77  5100.4 1544.16  5171.0 1544.39
  5192.4 1546.65  5221.4 1545.92  5231.5 1544.68  5251.7 1546.25  5332.4 1548.16
  5473.6 1553.57  5514.0 1554.03  5574.5 1556.80  5719.6 1560.18  5756.1 1562.36
#Mann=3,-1,0
  4487.1    0.05       0  5006.1    0.05       0  5013.1    0.05       0
Bank Sta=5006.1,5013.1
Exp/Cntr=0.3,0.1

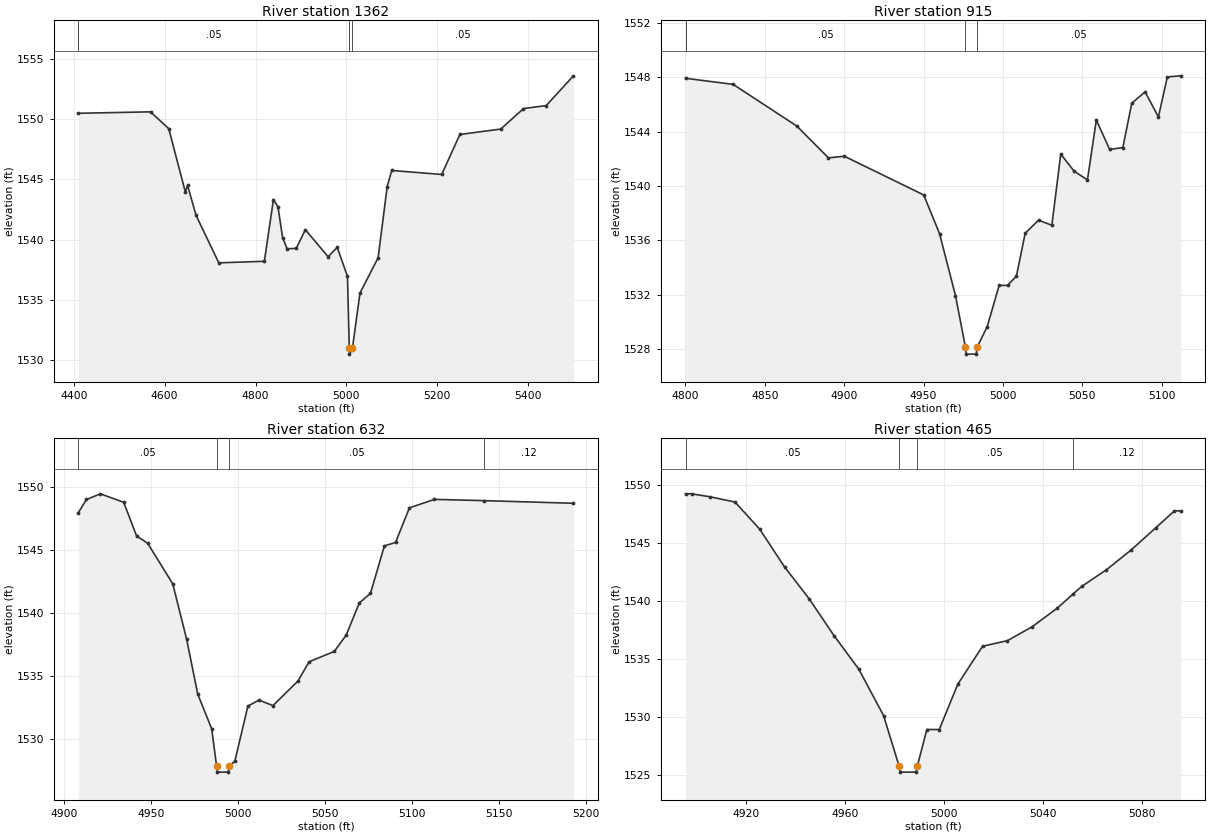
Type RM Length L Ch R = 1,1362,447,447,447
BEGIN DESCRIPTION:
Deadman 04 3.0
END DESCRIPTION:
XS GIS Cut Line= 3
      1613466.44      6938396.22      1614055.00      6938438.00
      1614554.96      6938438.00
#Sta/Elev= 30
  4409.9 1550.49  4568.9 1550.61  4609.0 1549.21  4645.5 1543.96  4650.5 1544.50
  4669.1 1542.01  4719.2 1538.07  4819.5 1538.20  4839.5 1543.33  4849.6 1542.70
  4859.6 1540.16  4869.6 1539.24  4889.7 1539.27  4909.7 1540.82  4959.8 1538.58
  4979.9 1539.35  5002.4 1536.96  5006.4 1530.99  5006.9 1530.49  5013.4 1530.99
  5029.9 1535.55  5069.9 1538.49  5089.9 1544.40  5099.9 1545.74  5209.9 1545.41
  5249.9 1548.73  5339.9 1549.18  5389.9 1550.88  5439.9 1551.13  5499.9 1553.60
#Mann=3,-1,0
  4409.9    0.05       0  5006.4    0.05       0  5013.4    0.05       0
Bank Sta=5006.4,5013.4
Exp/Cntr=0.3,0.1

Type RM Length L Ch R = 1,915,283,283,283
BEGIN DESCRIPTION:
Deadman 04 2.0
END DESCRIPTION:
XS GIS Cut Line= 3
      1614055.03      6938788.00      1614255.00      6938788.00
      1614305.01      6938888.02
#Sta/Elev= 30
  4800.1 1547.94  4830.1 1547.49  4870.1 1544.43  4890.1 1542.08  4900.1 1542.20
  4950.1 1539.35  4960.1 1536.49  4970.1 1531.94  4976.4 1528.13  4976.9 1527.63
  4983.2 1527.63  4983.7 1528.13  4990.1 1529.66  4997.6 1532.69  5002.9 1532.69
  5008.5 1533.38  5014.0 1536.53  5022.4 1537.49  5030.8 1537.12  5036.4 1542.36
  5044.8 1541.10  5053.2 1540.46  5058.8 1544.86  5067.2 1542.70  5075.5 1542.84
  5081.1 1546.10  5089.5 1546.94  5097.9 1545.09  5103.5 1548.04  5111.9 1548.12
#Mann=3,-1,0
  4800.1    0.05       0  4976.4    0.05       0  4983.7    0.05       0
Bank Sta=4976.4,4983.7
Exp/Cntr=0.3,0.1

Type RM Length L Ch R = 1,632,167,167,167
BEGIN DESCRIPTION:
Mapping XS 88b0191b
END DESCRIPTION:
XS GIS Cut Line= 2
      1614008.46      6938807.64      1614186.13      6939030.10
#Sta/Elev= 30
  4908.1 1547.96  4912.8 1549.01  4920.8 1549.46  4934.2 1548.79  4941.6 1546.12
  4948.0 1545.53  4962.4 1542.32  4970.4 1537.91  4976.8 1533.55  4984.8 1530.81
  4987.6 1527.87  4988.1 1527.37  4994.4 1527.37  4994.9 1527.87  4998.1 1528.23
  5005.6 1532.61  5012.0 1533.09  5020.0 1532.65  5034.4 1534.60  5040.8 1536.13
  5055.3 1536.95  5062.1 1538.24  5069.7 1540.80  5076.1 1541.56  5084.1 1545.33
  5090.5 1545.60  5098.5 1548.35  5112.9 1549.02  5141.1 1548.92  5192.8 1548.71
#Mann=4,-1,0
  4908.1    0.05       0  4987.6    0.05       0  4994.9    0.05       0
  5141.1    0.12       0
Bank Sta=4987.6,4994.9
Exp/Cntr=0.3,0.1

Type RM Length L Ch R = 1,465,0,0,0
BEGIN DESCRIPTION:
Deadman 04 1.0
END DESCRIPTION:
XS GIS Cut Line= 3
      1613855.02      6938988.00      1613955.00      6938988.00
      1614055.02      6938988.00
#Sta/Elev= 28
  4895.6 1549.25  4898.1 1549.25  4905.6 1548.99  4915.6 1548.54  4925.6 1546.19
  4935.6 1542.94  4945.6 1540.17  4955.6 1537.00  4965.6 1534.11  4975.6 1530.10
  4981.9 1525.72  4982.4 1525.22  4988.7 1525.22  4989.2 1525.72  4993.1 1528.90
  4998.1 1528.90  5005.6 1532.82  5015.6 1536.09  5025.6 1536.57  5035.6 1537.77
  5045.6 1539.35  5052.1 1540.59  5055.6 1541.25  5065.6 1542.69  5075.6 1544.40
  5085.6 1546.33  5093.1 1547.78  5095.6 1547.78
#Mann=4,-1,0
  4895.6    0.05       0  4981.9    0.05       0  4989.2    0.05       0
  5052.1    0.12       0
Bank Sta=4981.9,4989.2
Exp/Cntr=0.3,0.1

Chan Stop Cuts=-1