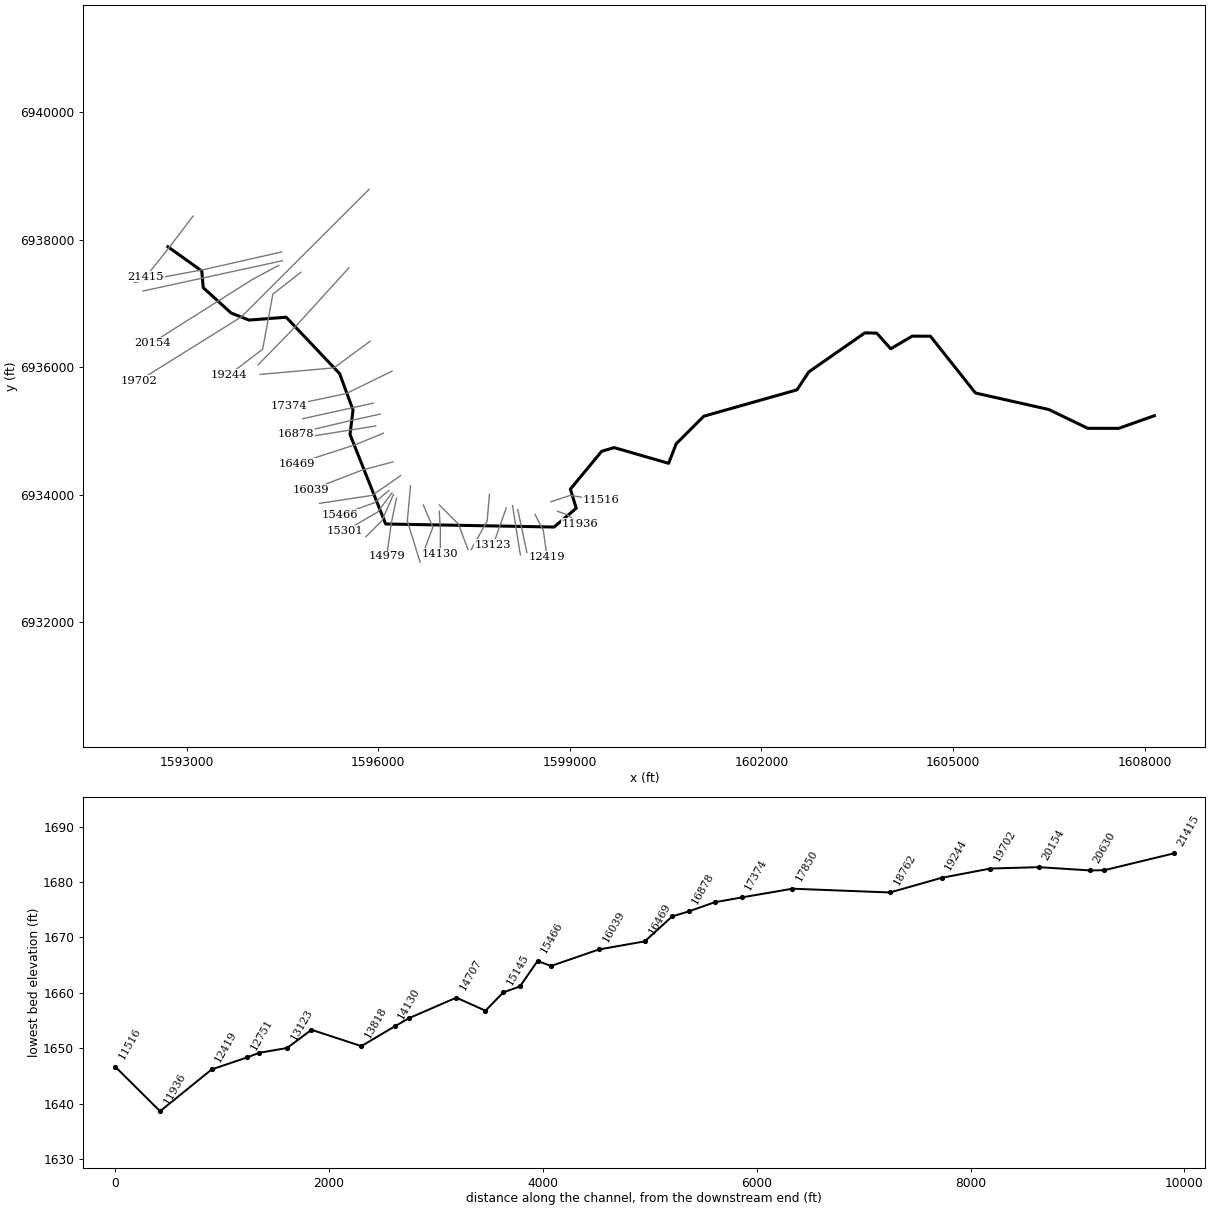
--- Deadman 06.prj (project) ---

Proj Title=Deadman 06 Base Level Engineering
Current Plan=p01
Default Exp/Contr=0.3,0.1
English Units
Geom File=g01
Flow File=f01
Plan File=p01
BEGIN DESCRIPTION:
Deadman 06
END DESCRIPTION:

--- Deadman 06.p01 (plan) ---

Plan Title=Multiple Run
Short Identifier=Multiple
Geom File=g01
Flow File=f01
Subcritical Flow
K Sum by GR= 0
Std Step Tol= 0.01
Critical Tol= 0.01
Num of Std Step Trials= 20
Max Error Tol= 0.3
Flow Tol Ratio= 0.001
Split Flow NTrial= 30
Split Flow Tol= 0.02
Split Flow Ratio= 0.02
Log Output Level= 0
Friction Slope Method= 1
Unsteady Friction Slope Method= 2
Unsteady Bridges Friction Slope Method= 1
Parabolic Critical Depth
Global Vel Dist=  1 , 1 , 1
Global Log Level= 0
CheckData=True
Encroach Param= -1, 0, 0, 0
BEGIN DESCRIPTION:
Multiple Run
END DESCRIPTION:

--- Deadman 06.f01 (steady flow) ---

Flow Title=Multiple
Number of Profiles=7
Profile Names=10-year,25-year,50-year,1pct_min,100-year,1pct_plu,500-year
River Rch & RM= Deadman 06,Reach-1,21415
     194     260     314     188     375     748     543
River Rch & RM= Deadman 06,Reach-1,20767
     275     376     457     276     551    1099     811
River Rch & RM= Deadman 06,Reach-1,15145
     405     567     702     432     861    1719    1315
River Rch & RM= Deadman 06,Reach-1,11322
     487     688     858     531    1059    2112    1635
River Rch & RM= Deadman 06,Reach-1,3080
     588     843    1060     662    1321    2637    2080
Boundary for River Rch & Prof#=Deadman 06,Reach-1,1
Up Type=0
Dn Type=3
Dn Slope=0.005
Boundary for River Rch & Prof#=Deadman 06,Reach-1,2
Up Type=0
Dn Type=3
Dn Slope=0.005
Boundary for River Rch & Prof#=Deadman 06,Reach-1,3
Up Type=0
Dn Type=3
Dn Slope=0.005
Boundary for River Rch & Prof#=Deadman 06,Reach-1,4
Up Type=0
Dn Type=3
Dn Slope=0.005
Boundary for River Rch & Prof#=Deadman 06,Reach-1,5
Up Type=0
Dn Type=3
Dn Slope=0.005
Boundary for River Rch & Prof#=Deadman 06,Reach-1,6
Up Type=0
Dn Type=3
Dn Slope=0.005
Boundary for River Rch & Prof#=Deadman 06,Reach-1,7
Up Type=0
Dn Type=3
Dn Slope=0.005

--- Deadman 06.g01 (geometry) ---

Geom Title=Existing Conditions

River Reach=Deadman 06,Reach-1
Reach XY= 30
      1592705.00      6937888.00      1593235.56      6937508.55
      1593258.07      6937246.30      1593695.32      6936848.76
      1593975.04      6936738.05      1594557.45      6936782.54
      1595394.48      6935897.79      1595604.24      6935327.31
      1595557.25      6934943.93      1596115.43      6933539.03
      1598753.53      6933491.55      1599099.94      6933785.70
      1599008.53      6934086.53      1599498.83      6934680.14
      1599694.31      6934737.23      1600546.72      6934491.06
      1600665.76      6934797.68      1601098.83      6935230.14
      1602557.70      6935643.36      1602741.76      6935924.39
      1603620.22      6936537.48      1603807.45      6936532.54
      1604025.34      6936287.68      1604360.93      6936485.76
      1604646.70      6936484.93      1605352.70      6935593.83
      1606499.06      6935335.74      1607110.94      6935040.26
      1607594.50      6935039.22      1608155.00      6935238.00

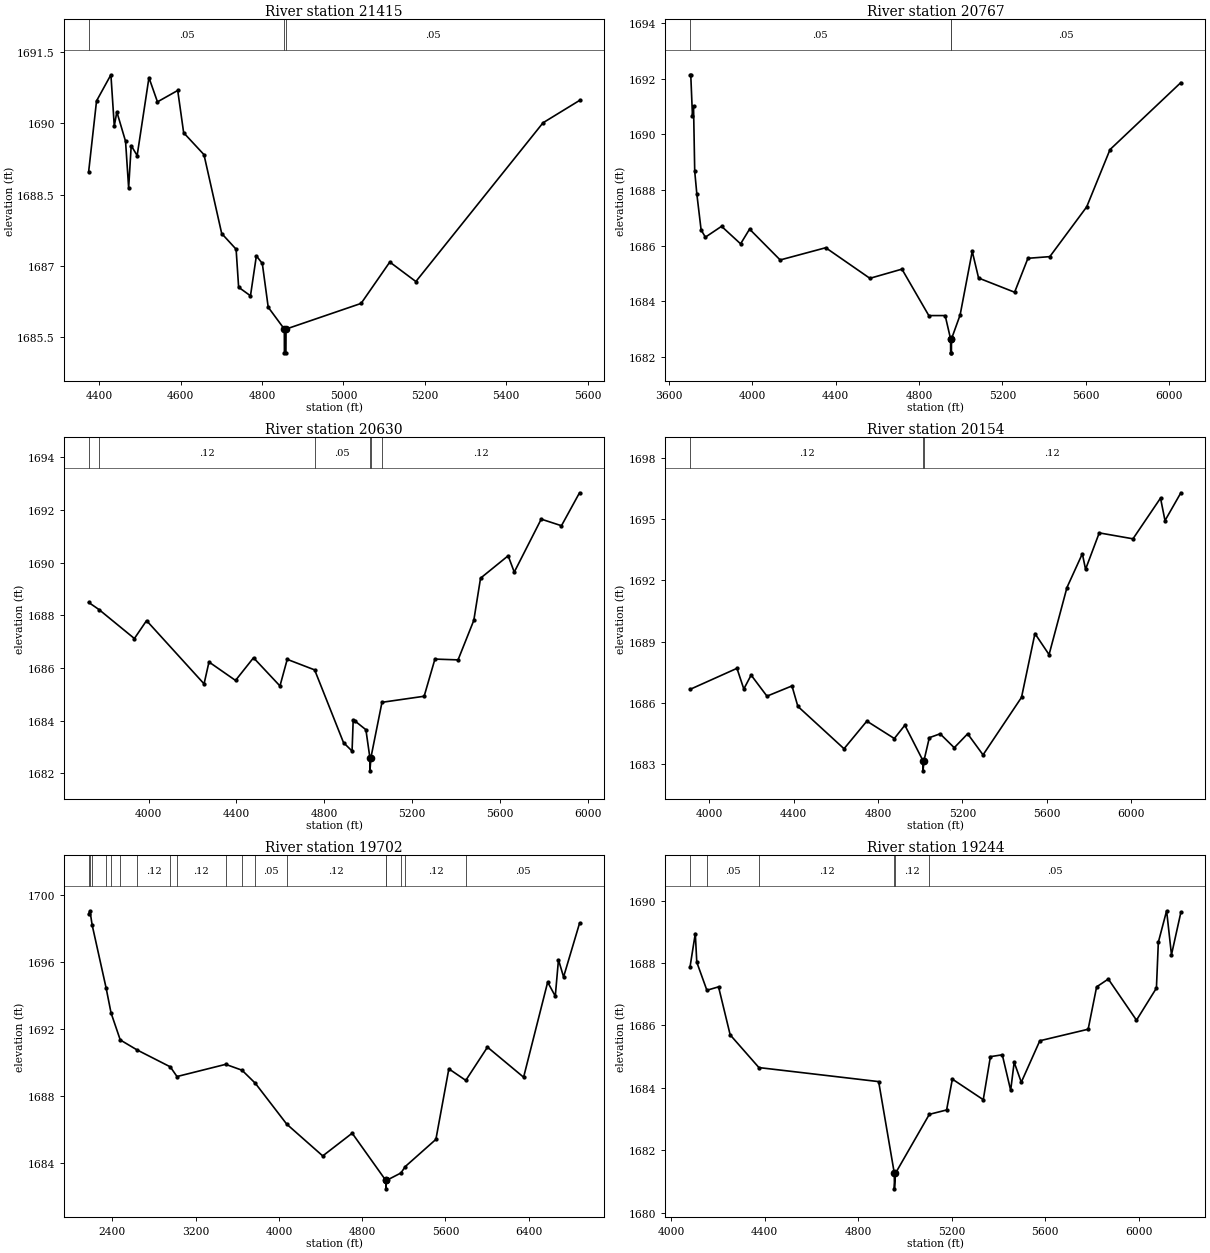
Type RM Length L Ch R = 1,21415,648,648,648
BEGIN DESCRIPTION:
Deadman 06 43.0
END DESCRIPTION:
XS GIS Cut Line= 3
      1593100.41      6938370.14      1592724.60      6937876.74
      1592360.87      6937417.07
#Sta/Elev= 30
  4373.9 1688.98  4393.3 1690.47  4428.6 1691.02  4436.9 1689.94  4443.2 1690.24
  4464.6 1689.62  4472.2 1688.64  4478.5 1689.53  4493.1 1689.32  4522.1 1690.96
  4543.0 1690.45  4592.8 1690.69  4607.4 1689.80  4657.3 1689.34  4700.9 1687.68
  4736.3 1687.35  4742.5 1686.55  4771.6 1686.37  4786.1 1687.21  4800.7 1687.05
  4815.2 1686.13  4854.8 1685.67  4855.0 1685.17  4858.7 1685.17  4859.0 1685.67
  5043.5 1686.21  5114.0 1687.08  5178.1 1686.67  5490.6 1690.01  5580.3 1690.48
#Mann=3,-1,0
  4373.9    0.05       0  4854.8    0.05       0  4859.0    0.05       0
Bank Sta=4854.8,4859
Exp/Cntr=0.3,0.1

Type RM Length L Ch R = 1,20767,137,137,137
BEGIN DESCRIPTION:
Mapping XS d285f2f7
END DESCRIPTION:
XS GIS Cut Line= 3
      1594487.11      6937806.66      1593292.64      6937535.82
      1592180.73      6937327.20
#Sta/Elev= 30
  3700.1 1692.14  3703.8 1692.14  3712.0 1690.66  3717.1 1691.02  3722.8 1688.67
  3733.0 1687.85  3753.5 1686.56  3774.0 1686.30  3851.6 1686.69  3943.0 1686.06
  3986.1 1686.59  4132.9 1685.48  4351.6 1685.92  4563.6 1684.82  4717.4 1685.15
  4846.4 1683.48  4924.9 1683.48  4950.9 1682.64  4951.2 1682.14  4954.9 1682.14
  4955.2 1682.64  4996.6 1683.50  5054.8 1685.79  5085.3 1684.83  5258.2 1684.32
  5322.1 1685.54  5427.2 1685.60  5604.2 1687.39  5716.1 1689.45  6056.2 1691.86
#Mann=3,-1,0
  3700.1    0.05       0  4950.9    0.03       0  4955.2    0.05       0
Bank Sta=4950.9,4955.2
Exp/Cntr=0.3,0.1

Type RM Length L Ch R = 1,20630,476,476,476
BEGIN DESCRIPTION:
Mapping XS 418f868e
END DESCRIPTION:
XS GIS Cut Line= 2
      1594498.51      6937668.90      1592314.58      6937193.39
#Sta/Elev= 30
  3726.9 1688.49  3773.9 1688.22  3935.2 1687.12  3990.6 1687.80  4252.4 1685.40
  4274.8 1686.23  4395.7 1685.53  4477.6 1686.39  4598.0 1685.32  4631.1 1686.33
  4755.9 1685.93  4887.4 1683.17  4926.3 1682.85  4931.4 1684.02  4938.1 1684.00
  4989.3 1683.66  5007.4 1682.60  5007.7 1682.10  5012.1 1682.60  5062.5 1684.70
  5254.5 1684.93  5303.6 1686.34  5408.9 1686.31  5480.6 1687.81  5511.3 1689.41
  5637.0 1690.26  5664.8 1689.64  5787.6 1691.65  5879.7 1691.40  5962.0 1692.65
#Mann=6,-1,0
  3726.9    0.05       0  3773.9    0.12       0  4755.9    0.05       0
  5007.4    0.05       0  5012.1    0.05       0  5062.5    0.12       0
Bank Sta=5007.4,5012.1
Exp/Cntr=0.3,0.1

Type RM Length L Ch R = 1,20154,452,452,452
BEGIN DESCRIPTION:
Mapping XS 9406c7a9
END DESCRIPTION:
XS GIS Cut Line= 3
      1594440.25      6937595.86      1594019.27      6937370.18
      1592458.35      6936381.59
#Sta/Elev= 30
  3909.3 1686.67  4131.8 1687.70  4164.3 1686.69  4198.9 1687.37  4273.9 1686.34
  4392.4 1686.84  4420.3 1685.84  4639.0 1683.77  4747.1 1685.12  4877.3 1684.27
  4927.1 1684.92  5012.8 1683.19  5013.2 1682.69  5017.7 1683.19  5043.0 1684.31
  5094.1 1684.50  5161.1 1683.82  5224.6 1684.50  5297.5 1683.47  5479.7 1686.28
  5543.3 1689.40  5610.2 1688.37  5695.0 1691.65  5767.9 1693.30  5783.1 1692.54
  5847.9 1694.32  6007.7 1694.03  6138.2 1696.02  6159.4 1694.92  6234.6 1696.28
#Mann=3,-1,0
  3909.3    0.12       0  5012.8    0.07       0  5017.7    0.12       0
Bank Sta=5012.8,5017.7
Exp/Cntr=0.3,0.1

Type RM Length L Ch R = 1,19702,458,458,458
BEGIN DESCRIPTION:
Deadman 06 40.0
END DESCRIPTION:
XS GIS Cut Line= 3
      1595854.97      6938787.97      1593855.00      6936788.00
      1592254.99      6935787.99
#Sta/Elev= 30
  2172.7 1698.89  2185.2 1699.08  2206.3 1698.23  2340.1 1694.47  2387.8 1692.97
  2476.3 1691.35  2638.6 1690.75  2956.9 1689.74  3021.3 1689.16  3488.9 1689.89
  3645.6 1689.54  3773.4 1688.76  4075.7 1686.31  4421.3 1684.41  4704.1 1685.77
  5027.5 1682.94  5027.9 1682.44  5032.4 1682.94  5172.6 1683.39  5213.4 1683.77
  5508.2 1685.40  5632.6 1689.62  5795.4 1688.93  6003.5 1690.92  6350.7 1689.12
  6581.9 1694.81  6655.0 1693.97  6685.6 1696.15  6734.6 1695.12  6887.9 1698.33
#Mann=18,-1,0
  2172.7    0.12       0  2185.2    0.05       0  2206.3    0.12       0
  2340.1    0.05       0  2387.8    0.12       0  2476.3    0.05       0
  2638.6    0.12       0  2956.9    0.05       0  3021.3    0.12       0
  3488.9    0.05       0  3645.6    0.12       0  3773.4    0.05       0
  4075.7    0.12       0  5027.5    0.07       0  5032.4    0.12       0
  5172.6    0.05       0  5213.4    0.12       0  5795.4    0.05       0
Bank Sta=5027.5,5032.4
Exp/Cntr=0.3,0.1

Type RM Length L Ch R = 1,19244,482,482,482
BEGIN DESCRIPTION:
Mapping XS b374b8ca
END DESCRIPTION:
XS GIS Cut Line= 4
      1594787.47      6937487.34      1594349.13      6937144.48
      1594188.54      6936280.77      1593659.53      6935877.50
#Sta/Elev= 30
  4081.0 1687.87  4103.7 1688.95  4110.1 1688.03  4153.3 1687.13  4203.2 1687.24
  4252.9 1685.70  4375.9 1684.65  4888.2 1684.20  4955.2 1681.26  4955.6 1680.76
  4960.2 1681.26  5105.0 1683.15  5178.9 1683.29  5203.5 1684.28  5335.7 1683.62
  5366.3 1685.00  5417.1 1685.06  5453.0 1683.92  5468.0 1684.82  5498.5 1684.18
  5577.7 1685.51  5784.5 1685.88  5820.8 1687.24  5870.7 1687.49  5991.3 1686.17
  6076.6 1687.20  6084.8 1688.67  6120.2 1689.68  6141.0 1688.27  6181.2 1689.63
#Mann=6,-1,0
  4081.0    0.12       0  4153.3    0.05       0  4375.9    0.12       0
  4955.2    0.07       0  4960.2    0.12       0  5105.0    0.05       0
Bank Sta=4955.2,4960.2
Exp/Cntr=0.3,0.1

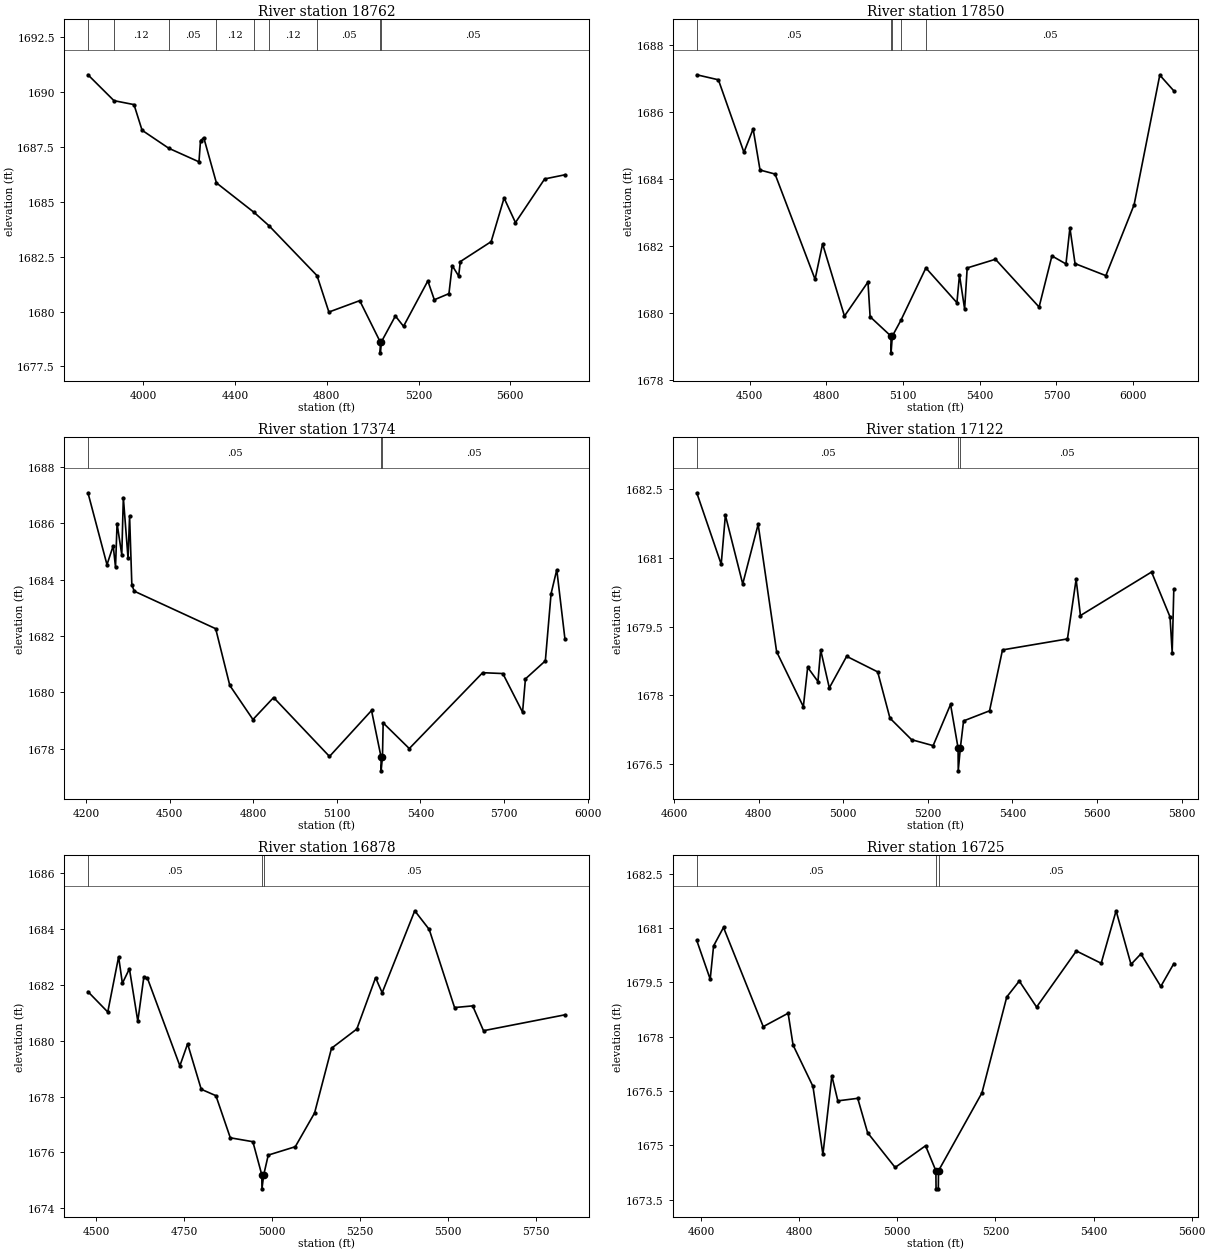
Type RM Length L Ch R = 1,18762,912,912,912
BEGIN DESCRIPTION:
Deadman 06 39.0
END DESCRIPTION:
XS GIS Cut Line= 3
      1595539.26      6937556.83      1594705.00      6936638.00
      1594119.96      6936037.70
#Sta/Elev= 30
  3759.2 1690.80  3872.5 1689.62  3959.9 1689.44  3995.1 1688.27  4111.3 1687.45
  4243.1 1686.83  4249.8 1687.80  4264.0 1687.93  4319.1 1685.87  4483.8 1684.52
  4548.0 1683.92  4757.7 1681.64  4809.4 1679.98  4943.8 1680.50  5033.1 1678.62
  5033.5 1678.12  5038.1 1678.62  5099.2 1679.80  5134.7 1679.33  5240.7 1681.40
  5268.9 1680.54  5332.7 1680.82  5346.8 1682.10  5375.1 1681.62  5382.1 1682.28
  5516.6 1683.19  5573.0 1685.18  5622.6 1684.06  5749.9 1686.05  5838.5 1686.24
#Mann=9,-1,0
  3759.2    0.05       0  3872.5    0.12       0  4111.3    0.05       0
  4319.1    0.12       0  4483.8    0.05       0  4548.0    0.12       0
  4757.7    0.05       0  5033.1    0.05       0  5038.1    0.05       0
Bank Sta=5033.1,5038.1
Exp/Cntr=0.3,0.1

Type RM Length L Ch R = 1,17850,476,476,476
BEGIN DESCRIPTION:
Deadman 06 38.0
END DESCRIPTION:
XS GIS Cut Line= 3
      1595873.45      6936406.64      1595305.00      6935988.00
      1594150.38      6935885.80
#Sta/Elev= 30
  4293.7 1687.12  4378.3 1686.97  4478.1 1684.80  4514.1 1685.50  4541.1 1684.27
  4599.7 1684.15  4756.3 1681.00  4785.6 1682.06  4871.2 1679.90  4963.1 1680.92
  4971.5 1679.88  5053.0 1679.30  5053.4 1678.80  5058.3 1679.30  5091.6 1679.77
  5189.5 1681.34  5310.9 1680.30  5320.9 1681.13  5341.0 1680.11  5351.0 1681.34
  5461.5 1681.60  5632.1 1680.17  5682.3 1681.70  5737.2 1681.46  5752.6 1682.54
  5772.7 1681.47  5893.1 1681.11  6003.6 1683.23  6104.0 1687.11  6158.8 1686.64
#Mann=5,-1,0
  4293.7    0.05       0  5053.0    0.05       0  5058.3    0.05       0
  5091.6    0.12       0  5189.5    0.05       0
Bank Sta=5053,5058.3
Exp/Cntr=0.3,0.1

Type RM Length L Ch R = 1,17374,252,252,252
BEGIN DESCRIPTION:
Deadman 06 37.0
END DESCRIPTION:
XS GIS Cut Line= 3
      1596216.30      6935937.88      1595505.00      6935588.00
      1594606.11      6935395.36
#Sta/Elev= 30
  4207.1 1687.08  4275.4 1684.53  4297.7 1685.20  4306.0 1684.44  4311.6 1685.99
  4328.5 1684.88  4334.1 1686.91  4351.0 1684.75  4356.5 1686.26  4364.6 1683.81
  4373.4 1683.59  4665.5 1682.26  4716.1 1680.25  4799.2 1679.04  4873.4 1679.82
  5073.9 1677.73  5224.8 1679.36  5258.8 1677.72  5259.2 1677.22  5264.1 1677.72
  5266.5 1678.92  5360.3 1678.01  5623.6 1680.70  5696.0 1680.67  5766.8 1679.30
  5777.1 1680.48  5848.6 1681.12  5869.1 1683.50  5889.6 1684.35  5919.1 1681.88
#Mann=3,-1,0
  4207.1    0.05       0  5258.8    0.05       0  5264.1    0.05       0
Bank Sta=5258.8,5264.1
Exp/Cntr=0.3,0.1

Type RM Length L Ch R = 1,17122,244,244,244
BEGIN DESCRIPTION:
Mapping XS f64ecefd
END DESCRIPTION:
XS GIS Cut Line= 2
      1595921.15      6935434.41      1594819.41      6935191.50
#Sta/Elev= 30
  4653.5 1682.42  4711.3 1680.86  4721.2 1681.93  4762.2 1680.43  4798.7 1681.73
  4842.4 1678.95  4905.6 1677.75  4915.8 1678.61  4940.1 1678.30  4946.5 1678.99
  4967.0 1678.16  5008.0 1678.85  5081.4 1678.51  5110.4 1677.50  5161.6 1677.03
  5212.5 1676.90  5253.7 1677.80  5271.5 1676.85  5271.9 1676.35  5276.9 1676.85
  5284.5 1677.44  5345.9 1677.66  5376.6 1678.99  5530.2 1679.23  5550.7 1680.53
  5560.9 1679.74  5729.1 1680.69  5772.8 1679.71  5777.9 1678.93  5781.7 1680.31
#Mann=3,-1,0
  4653.5    0.05       0  5271.5    0.03       0  5276.9    0.05       0
Bank Sta=5271.5,5276.9
Exp/Cntr=0.3,0.1

Type RM Length L Ch R = 1,16878,153,153,153
BEGIN DESCRIPTION:
Deadman 06 36.0
END DESCRIPTION:
XS GIS Cut Line= 3
      1596030.02      6935263.00      1595522.31      6935151.43
      1594709.88      6934957.00
#Sta/Elev= 30
  4476.3 1681.76  4532.6 1681.03  4563.4 1683.01  4574.1 1682.06  4594.1 1682.58
  4617.9 1680.70  4635.0 1682.28  4645.3 1682.24  4737.4 1679.10  4759.4 1679.89
  4798.1 1678.26  4839.8 1678.03  4880.7 1676.52  4944.8 1676.38  4970.2 1675.19
  4970.6 1674.69  4975.6 1675.19  4988.5 1675.90  5065.3 1676.20  5120.1 1677.41
  5168.2 1679.73  5240.1 1680.42  5293.4 1682.26  5312.1 1681.72  5404.7 1684.66
  5445.8 1683.99  5517.8 1681.19  5569.2 1681.25  5600.0 1680.36  5831.5 1680.93
#Mann=3,-1,0
  4476.3    0.05       0  4970.2    0.03       0  4975.6    0.05       0
Bank Sta=4970.2,4975.6
Exp/Cntr=0.3,0.1

Type RM Length L Ch R = 1,16725,256,256,256
BEGIN DESCRIPTION:
Mapping XS b84a4fea
END DESCRIPTION:
XS GIS Cut Line= 2
      1595958.83      6935077.05      1594998.88      6934923.19
#Sta/Elev= 30
  4591.4 1680.66  4618.8 1679.59  4625.7 1680.51  4645.9 1681.02  4726.9 1678.28
  4777.6 1678.65  4787.7 1677.77  4828.2 1676.63  4848.5 1674.75  4866.7 1676.92
  4878.9 1676.23  4919.4 1676.30  4939.6 1675.35  4995.7 1674.39  5057.7 1674.99
  5078.7 1674.30  5079.1 1673.80  5083.7 1673.80  5084.1 1674.30  5172.6 1676.45
  5223.2 1679.10  5248.7 1679.54  5284.0 1678.82  5365.0 1680.37  5415.6 1680.03
  5446.0 1681.48  5476.4 1680.00  5496.6 1680.29  5537.1 1679.39  5563.6 1680.02
#Mann=3,-1,0
  4591.4    0.05       0  5078.7    0.03       0  5084.1    0.05       0
Bank Sta=5078.7,5084.1
Exp/Cntr=0.3,0.1

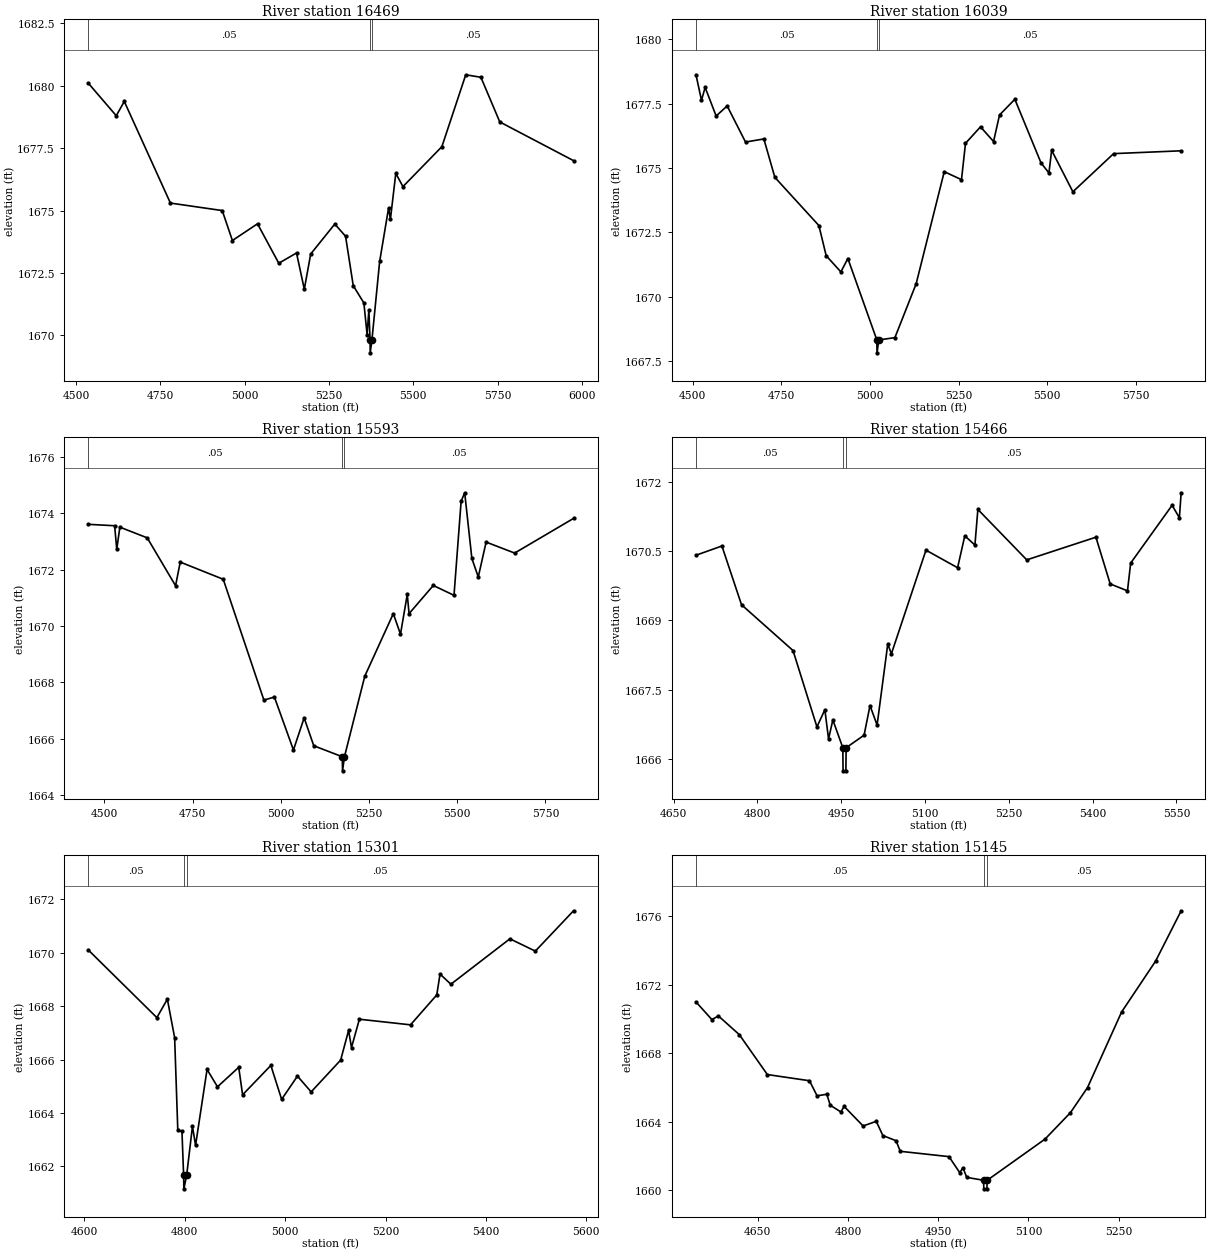
Type RM Length L Ch R = 1,16469,430,430,430
BEGIN DESCRIPTION:
Deadman 06 35.0
END DESCRIPTION:
XS GIS Cut Line= 3
      1596080.03      6934963.01      1595655.00      6934788.00
      1594723.67      6934484.75
#Sta/Elev= 30
  4536.1 1680.10  4618.8 1678.80  4642.7 1679.37  4779.5 1675.30  4933.2 1675.00
  4963.3 1673.80  5037.8 1674.47  5100.9 1672.89  5153.5 1673.30  5176.6 1671.85
  5195.6 1673.26  5267.1 1674.46  5299.0 1673.97  5321.8 1671.99  5353.3 1671.30
  5362.9 1670.03  5368.1 1671.02  5371.7 1669.80  5372.1 1669.30  5377.1 1669.80
  5400.1 1672.96  5426.7 1675.11  5432.0 1674.65  5448.0 1676.49  5469.2 1675.96
  5584.7 1677.56  5655.5 1680.44  5700.4 1680.34  5756.5 1678.55  5975.2 1677.00
#Mann=3,-1,0
  4536.1    0.05       0  5371.7    0.03       0  5377.1    0.05       0
Bank Sta=5371.7,5377.1
Exp/Cntr=0.3,0.1

Type RM Length L Ch R = 1,16039,446,446,446
BEGIN DESCRIPTION:
Deadman 06 34.0
END DESCRIPTION:
XS GIS Cut Line= 3
      1596229.96      6934512.99      1595755.00      6934388.00
      1594937.37      6934072.28
#Sta/Elev= 30
  4509.7 1678.62  4525.2 1677.63  4535.5 1678.13  4566.5 1677.02  4597.6 1677.41
  4649.3 1676.01  4701.0 1676.13  4732.0 1674.64  4856.1 1672.77  4876.7 1671.60
  4918.1 1670.97  4937.8 1671.49  5019.5 1668.33  5020.0 1667.83  5025.0 1668.33
  5070.4 1668.42  5130.3 1670.51  5209.5 1674.86  5258.1 1674.55  5269.4 1675.96
  5311.7 1676.60  5348.5 1676.03  5365.3 1677.06  5408.5 1677.67  5482.3 1675.20
  5504.6 1674.81  5512.2 1675.69  5572.1 1674.08  5686.9 1675.56  5877.3 1675.67
#Mann=3,-1,0
  4509.7    0.05       0  5019.5    0.03       0  5025.0    0.05       0
Bank Sta=5019.5,5025
Exp/Cntr=0.3,0.1

Type RM Length L Ch R = 1,15593,127,127,127
BEGIN DESCRIPTION:
Deadman 06 33.0
END DESCRIPTION:
XS GIS Cut Line= 3
      1596348.66      6934297.23      1595905.00      6933988.00
      1595080.01      6933863.00
#Sta/Elev= 30
  4454.6 1673.61  4529.0 1673.56  4535.1 1672.73  4543.9 1673.51  4621.5 1673.13
  4701.8 1671.43  4715.0 1672.27  4836.9 1671.66  4952.2 1667.37  4981.9 1667.48
  5035.9 1665.60  5066.2 1666.74  5093.5 1665.75  5174.5 1665.36  5175.0 1664.86
  5180.5 1665.36  5238.1 1668.22  5319.0 1670.44  5339.3 1669.71  5358.5 1671.12
  5363.6 1670.44  5432.3 1671.44  5491.0 1671.09  5511.2 1674.43  5521.3 1674.73
  5541.6 1672.40  5559.8 1671.74  5582.0 1672.98  5662.9 1672.59  5829.8 1673.82
#Mann=3,-1,0
  4454.6    0.05       0  5174.5    0.05       0  5180.5    0.05       0
Bank Sta=5174.5,5180.5
Exp/Cntr=0.3,0.1

Type RM Length L Ch R = 1,15466,165,165,165
BEGIN DESCRIPTION:
Mapping XS 8b1c1fe4
END DESCRIPTION:
XS GIS Cut Line= 3
      1596164.16      6934064.12      1595940.44      6933871.57
      1595399.72      6933680.95
#Sta/Elev= 30
  4690.0 1670.41  4736.4 1670.61  4771.5 1669.34  4863.7 1668.35  4906.5 1666.70
  4920.7 1667.07  4927.3 1666.44  4935.0 1666.85  4952.8 1666.25  4953.3 1665.75
  4958.3 1665.75  4958.8 1666.25  4990.9 1666.52  5001.5 1667.16  5014.2 1666.74
  5033.3 1668.49  5039.8 1668.28  5101.7 1670.52  5158.3 1670.14  5171.2 1670.83
  5189.3 1670.63  5194.6 1671.40  5282.1 1670.31  5405.9 1670.80  5431.5 1669.79
  5462.4 1669.64  5468.1 1670.24  5542.3 1671.49  5555.3 1671.22  5558.5 1671.76
#Mann=3,-1,0
  4690.0    0.05       0  4952.8    0.05       0  4958.8    0.05       0
Bank Sta=4952.8,4958.8
Exp/Cntr=0.3,0.1

Type RM Length L Ch R = 1,15301,156,156,156
BEGIN DESCRIPTION:
Mapping XS a09024f6
END DESCRIPTION:
XS GIS Cut Line= 3
      1596215.54      6934027.47      1595988.12      6933724.85
      1595479.16      6933430.09
#Sta/Elev= 30
  4607.8 1670.10  4744.3 1667.57  4765.2 1668.26  4779.7 1666.82  4786.0 1663.35
  4794.3 1663.31  4797.6 1661.66  4798.1 1661.16  4803.6 1661.66  4815.2 1663.50
  4821.4 1662.79  4844.3 1665.63  4865.1 1664.98  4907.4 1665.71  4915.1 1664.68
  4971.4 1665.78  4992.9 1664.51  5024.4 1665.38  5051.7 1664.79  5110.5 1665.98
  5126.3 1667.09  5132.1 1666.45  5147.8 1667.51  5249.7 1667.30  5302.0 1668.42
  5308.5 1669.20  5330.1 1668.82  5447.7 1670.52  5498.4 1670.06  5574.5 1671.57
#Mann=3,-1,0
  4607.8    0.05       0  4797.6    0.03       0  4803.6    0.05       0
Bank Sta=4797.6,4803.6
Exp/Cntr=0.3,0.1

Type RM Length L Ch R = 1,15145,166,166,166
BEGIN DESCRIPTION:
Deadman 06 32.0
END DESCRIPTION:
XS GIS Cut Line= 3
      1596237.60      6934002.14      1596055.00      6933588.00
      1595804.97      6933337.97
#Sta/Elev= 30
  4547.6 1670.99  4574.0 1669.96  4584.9 1670.17  4619.6 1669.08  4666.2 1666.75
  4736.2 1666.39  4748.8 1665.51  4765.0 1665.60  4770.7 1664.96  4788.3 1664.57
  4793.8 1664.89  4825.3 1663.75  4847.2 1664.02  4858.1 1663.19  4880.0 1662.89
  4887.1 1662.27  4968.0 1661.96  4985.8 1661.03  4991.3 1661.30  4997.5 1660.75
  5025.4 1660.58  5025.9 1660.08  5031.0 1660.08  5031.5 1660.58  5127.5 1662.98
  5169.9 1664.53  5198.2 1665.99  5254.8 1670.40  5311.3 1673.37  5353.8 1676.31
#Mann=3,-1,0
  4547.6    0.05       0  5025.4    0.05       0  5031.5    0.05       0
Bank Sta=5025.4,5031.5
Exp/Cntr=0.3,0.1

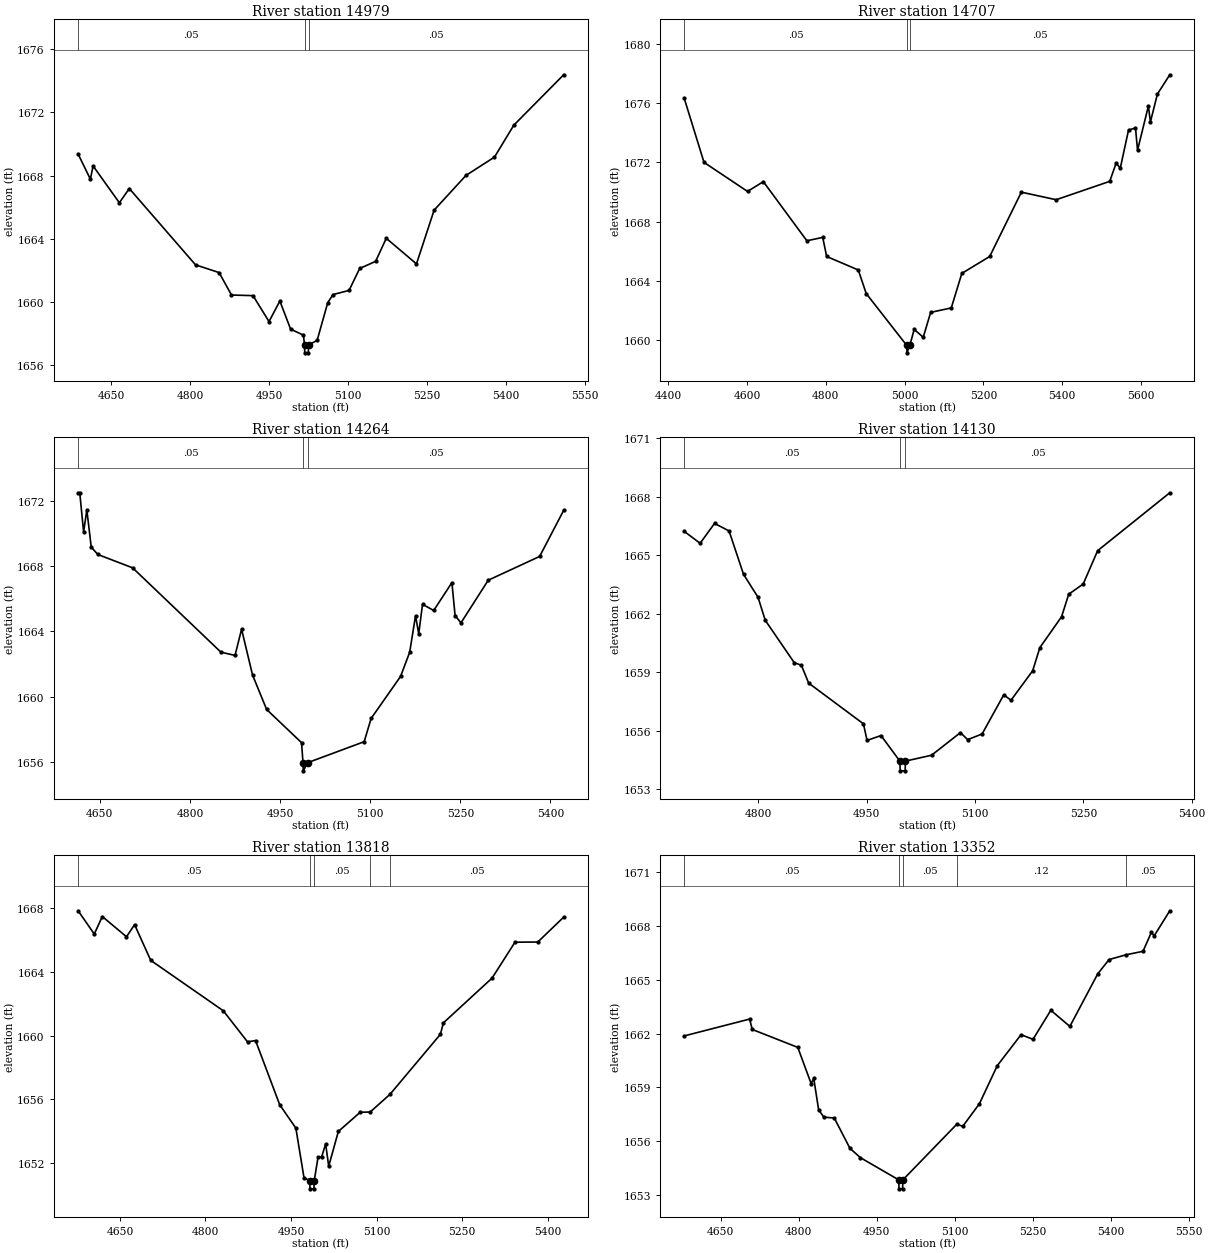
Type RM Length L Ch R = 1,14979,272,272,272
BEGIN DESCRIPTION:
Mapping XS 1fd3fcb8
END DESCRIPTION:
XS GIS Cut Line= 3
      1596285.34      6933943.11      1596204.60      6933557.68
      1596131.68      6933034.22
#Sta/Elev= 30
  4587.5 1669.36  4610.8 1667.77  4615.9 1668.61  4665.8 1666.28  4684.7 1667.18
  4810.5 1662.35  4855.3 1661.86  4878.8 1660.44  4919.7 1660.40  4950.1 1658.76
  4970.7 1660.06  4991.1 1658.28  5015.5 1657.90  5017.5 1657.28  5018.0 1656.78
  5024.7 1656.78  5025.2 1657.28  5041.5 1657.57  5061.7 1659.96  5071.8 1660.47
  5102.1 1660.73  5122.3 1662.12  5152.6 1662.57  5172.8 1664.03  5230.2 1662.41
  5263.7 1665.81  5324.2 1668.01  5378.4 1669.17  5415.1 1671.19  5509.8 1674.38
#Mann=3,-1,0
  4587.5    0.05       0  5017.5    0.03       0  5025.2    0.05       0
Bank Sta=5017.5,5025.2
Exp/Cntr=0.3,0.1

Type RM Length L Ch R = 1,14707,443,443,443
BEGIN DESCRIPTION:
Deadman 06 31.0
END DESCRIPTION:
XS GIS Cut Line= 3
      1596505.00      6934138.02      1596455.00      6933588.00
      1596655.01      6932937.96
#Sta/Elev= 30
  4440.7 1676.31  4490.9 1671.99  4601.4 1670.03  4641.5 1670.69  4752.0 1666.70
  4792.2 1666.93  4802.2 1665.64  4882.5 1664.73  4902.6 1663.14  5005.5 1659.64
  5006.0 1659.14  5013.2 1659.64  5024.4 1660.72  5047.3 1660.19  5066.2 1661.87
  5118.5 1662.17  5145.3 1664.50  5216.0 1665.64  5296.4 1669.98  5384.7 1669.47
  5520.7 1670.71  5537.0 1671.94  5547.5 1671.60  5568.4 1674.17  5586.1 1674.31
  5591.3 1672.81  5618.8 1675.79  5624.0 1674.72  5641.7 1676.60  5673.1 1677.90
#Mann=3,-1,0
  4440.7    0.05       0  5005.5    0.03       0  5013.2    0.05       0
Bank Sta=5005.5,5013.2
Exp/Cntr=0.3,0.1

Type RM Length L Ch R = 1,14264,134,134,134
BEGIN DESCRIPTION:
Deadman 06 30.0
END DESCRIPTION:
XS GIS Cut Line= 3
      1596704.99      6933838.03      1596855.00      6933488.00
      1596705.01      6933088.02
#Sta/Elev= 30
  4614.0 1672.52  4616.7 1672.52  4623.1 1670.12  4628.5 1671.46  4635.8 1669.19
  4646.7 1668.73  4704.7 1667.91  4851.6 1662.73  4875.1 1662.53  4886.0 1664.14
  4904.2 1661.33  4927.7 1659.21  4985.8 1657.17  4988.2 1655.94  4988.7 1655.44
  4995.9 1655.94  5090.0 1657.23  5101.6 1658.66  5150.6 1661.24  5165.7 1662.72
  5175.5 1664.97  5180.8 1663.86  5187.1 1665.67  5205.7 1665.29  5236.0 1667.00
  5241.3 1664.98  5251.1 1664.53  5296.5 1667.15  5382.0 1668.61  5422.0 1671.44
#Mann=3,-1,0
  4614.0    0.05       0  4988.2    0.03       0  4995.9    0.05       0
Bank Sta=4988.2,4995.9
Exp/Cntr=0.3,0.1

Type RM Length L Ch R = 1,14130,312,312,312
BEGIN DESCRIPTION:
Mapping XS b8afa446
END DESCRIPTION:
XS GIS Cut Line= 3
      1596954.60      6933739.97      1596972.83      6933445.70
      1596970.23      6933068.14
#Sta/Elev= 30
  4697.2 1666.23  4719.2 1665.62  4739.2 1666.64  4759.3 1666.25  4779.3 1664.03
  4799.4 1662.85  4809.4 1661.67  4849.5 1659.50  4859.5 1659.36  4869.5 1658.45
  4945.4 1656.36  4950.4 1655.51  4969.7 1655.76  4995.8 1654.45  4996.3 1653.95
  5003.1 1653.95  5003.6 1654.45  5039.7 1654.75  5079.7 1655.91  5089.7 1655.55
  5109.7 1655.84  5139.7 1657.85  5149.7 1657.57  5179.7 1659.08  5189.7 1660.27
  5219.7 1661.85  5229.7 1663.01  5249.7 1663.53  5269.7 1665.24  5369.6 1668.21
#Mann=3,-1,0
  4697.2    0.05       0  4995.8    0.03       0  5003.6    0.05       0
Bank Sta=4995.8,5003.6
Exp/Cntr=0.3,0.1

Type RM Length L Ch R = 1,13818,466,466,466
BEGIN DESCRIPTION:
Deadman 06 29.0
END DESCRIPTION:
XS GIS Cut Line= 3
      1596955.02      6933837.98      1597255.00      6933538.00
      1597404.99      6933138.04
#Sta/Elev= 30
  4576.8 1667.83  4605.1 1666.37  4619.2 1667.47  4661.6 1666.20  4675.8 1666.96
  4704.1 1664.72  4831.3 1661.56  4873.8 1659.61  4887.9 1659.69  4930.3 1655.66
  4958.6 1654.20  4972.8 1651.10  4982.9 1650.89  4983.4 1650.39  4990.3 1650.39
  4990.8 1650.89  4997.5 1652.38  5003.7 1652.38  5010.8 1653.21  5016.2 1651.81
  5033.1 1653.99  5071.3 1655.19  5089.0 1655.21  5123.7 1656.32  5212.0 1660.08
  5217.3 1660.80  5302.7 1663.61  5342.8 1665.86  5382.8 1665.87  5428.2 1667.43
#Mann=5,-1,0
  4576.8    0.05       0  4982.9    0.05       0  4990.8    0.05       0
  5089.0    0.12       0  5123.7    0.05       0
Bank Sta=4982.9,4990.8
Exp/Cntr=0.3,0.1

Type RM Length L Ch R = 1,13352,229,229,229
BEGIN DESCRIPTION:
Deadman 06 28.0
END DESCRIPTION:
XS GIS Cut Line= 3
      1597741.06      6934005.55      1597705.00      6933588.00
      1597454.99      6933137.99
#Sta/Elev= 30
  4579.9 1661.87  4705.7 1662.81  4710.7 1662.23  4798.3 1661.23  4824.0 1659.21
  4829.0 1659.50  4838.4 1657.75  4848.4 1657.34  4868.5 1657.29  4898.6 1655.60
  4918.7 1655.08  4992.5 1653.84  4993.0 1653.34  4999.9 1653.34  5000.4 1653.84
  5104.0 1656.94  5115.7 1656.83  5147.7 1658.09  5182.0 1660.21  5227.8 1661.94
  5250.7 1661.68  5285.0 1663.30  5321.6 1662.40  5375.4 1665.34  5397.1 1666.13
  5429.0 1666.39  5462.3 1666.59  5478.3 1667.64  5484.0 1667.46  5513.8 1668.85
#Mann=5,-1,0
  4579.9    0.05       0  4992.5    0.03       0  5000.4    0.05       0
  5104.0    0.12       0  5429.0    0.05       0
Bank Sta=4992.5,5000.4
Exp/Cntr=0.3,0.1

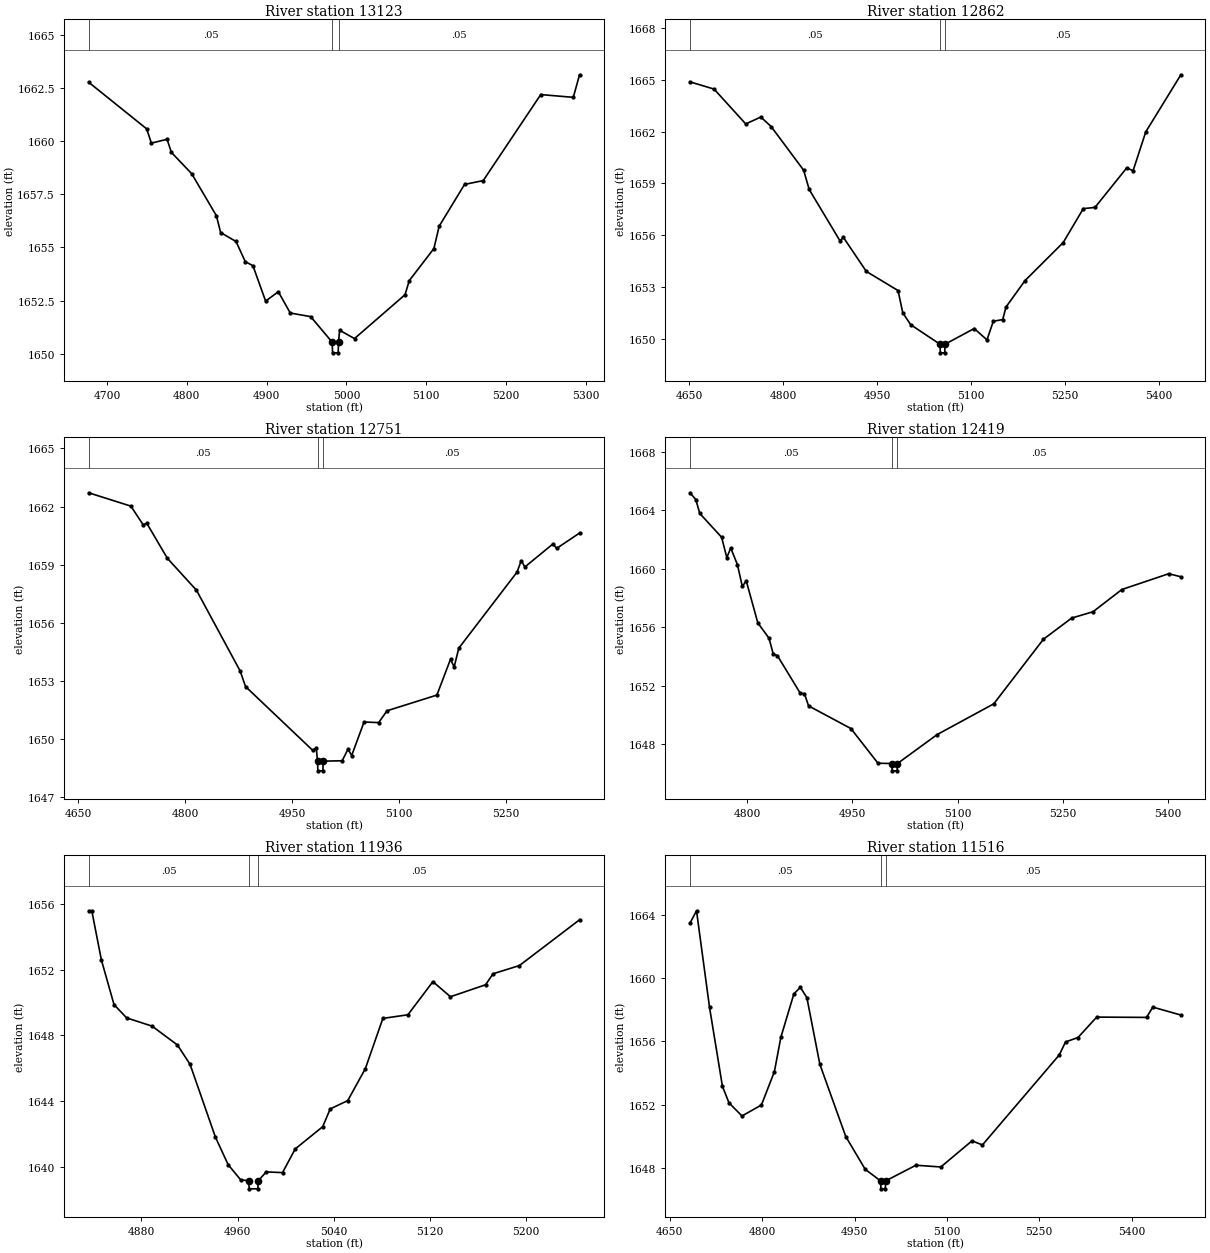
Type RM Length L Ch R = 1,13123,261,261,261
BEGIN DESCRIPTION:
Mapping XS 78918f61
END DESCRIPTION:
XS GIS Cut Line= 2
      1598004.09      6933792.06      1597798.66      6933212.18
#Sta/Elev= 30
  4676.9 1662.76  4749.6 1660.57  4755.5 1659.90  4775.2 1660.08  4780.5 1659.47
  4806.1 1658.46  4837.0 1656.49  4842.3 1655.70  4861.6 1655.28  4873.1 1654.34
  4882.8 1654.14  4898.7 1652.48  4914.6 1652.92  4929.6 1651.92  4955.2 1651.75
  4982.1 1650.55  4982.6 1650.05  4989.6 1650.05  4990.1 1650.55  4991.4 1651.11
  5010.1 1650.72  5073.4 1652.78  5078.7 1653.44  5109.6 1654.95  5116.2 1656.00
  5148.0 1657.96  5171.4 1658.14  5243.5 1662.18  5284.3 1662.05  5292.1 1663.11
#Mann=3,-1,0
  4676.9    0.05       0  4982.1    0.03       0  4990.1    0.05       0
Bank Sta=4982.1,4990.1
Exp/Cntr=0.3,0.1

Type RM Length L Ch R = 1,12862,111,111,111
BEGIN DESCRIPTION:
Deadman 06 27.0
END DESCRIPTION:
XS GIS Cut Line= 3
      1598103.04      6933825.91      1598155.00      6933488.00
      1598225.39      6933052.73
#Sta/Elev= 30
  4651.7 1664.89  4690.1 1664.47  4740.6 1662.45  4764.6 1662.85  4781.1 1662.30
  4832.9 1659.77  4841.8 1658.65  4891.1 1655.66  4896.2 1655.88  4932.9 1653.90
  4983.5 1652.79  4991.0 1651.50  5003.7 1650.81  5050.4 1649.68  5050.9 1649.18
  5057.9 1649.18  5058.4 1649.68  5105.0 1650.59  5125.3 1649.93  5135.4 1651.01
  5150.4 1651.11  5155.7 1651.84  5186.0 1653.37  5246.8 1655.57  5278.9 1657.54
  5297.5 1657.61  5348.1 1659.90  5358.3 1659.74  5378.5 1661.99  5434.5 1665.30
#Mann=3,-1,0
  4651.7    0.05       0  5050.4    0.05       0  5058.4    0.05       0
Bank Sta=5050.4,5058.4
Exp/Cntr=0.3,0.1

Type RM Length L Ch R = 1,12751,332,332,332
BEGIN DESCRIPTION:
Mapping XS aa49d7a8
END DESCRIPTION:
XS GIS Cut Line= 2
      1598183.78      6933765.98      1598326.84      6933092.30
#Sta/Elev= 30
  4664.8 1662.71  4724.1 1662.02  4741.2 1661.06  4746.3 1661.14  4775.2 1659.33
  4816.1 1657.68  4877.4 1653.51  4884.9 1652.71  4979.1 1649.42  4984.2 1649.52
  4985.9 1648.86  4986.4 1648.36  4993.4 1648.36  4993.9 1648.86  5020.5 1648.88
  5028.7 1649.48  5033.8 1649.15  5051.2 1650.88  5071.7 1650.85  5083.4 1651.46
  5153.4 1652.27  5172.5 1654.12  5177.6 1653.72  5184.1 1654.69  5265.9 1658.62
  5271.7 1659.21  5276.8 1658.88  5316.2 1660.07  5321.4 1659.84  5353.5 1660.63
#Mann=3,-1,0
  4664.8    0.05       0  4985.9    0.05       0  4993.9    0.05       0
Bank Sta=4985.9,4993.9
Exp/Cntr=0.3,0.1

Type RM Length L Ch R = 1,12419,483,483,483
BEGIN DESCRIPTION:
Deadman 06 26.0
END DESCRIPTION:
XS GIS Cut Line= 3
      1598454.99      6933688.02      1598584.70      6933438.29
      1598642.10      6933023.85
#Sta/Elev= 30
  4718.6 1665.19  4726.9 1664.73  4732.5 1663.78  4763.7 1662.15  4771.1 1660.76
  4776.7 1661.42  4786.2 1660.28  4793.2 1658.79  4798.8 1659.17  4815.3 1656.30
  4831.3 1655.25  4837.4 1654.15  4843.1 1654.07  4876.0 1651.48  4881.7 1651.47
  4887.6 1650.63  4948.0 1649.08  4986.6 1646.71  5006.3 1646.69  5006.8 1646.19
  5013.9 1646.19  5014.4 1646.69  5071.0 1648.67  5151.7 1650.77  5222.4 1655.18
  5262.8 1656.63  5293.1 1657.06  5334.3 1658.58  5401.1 1659.66  5418.4 1659.45
#Mann=3,-1,0
  4718.6    0.05       0  5006.3    0.05       0  5014.4    0.05       0
Bank Sta=5006.3,5014.4
Exp/Cntr=0.3,0.1

Type RM Length L Ch R = 1,11936,420,420,420
BEGIN DESCRIPTION:
Deadman 06 25.0
END DESCRIPTION:
XS GIS Cut Line= 3
      1598804.99      6933738.00      1598955.00      6933688.00
      1599154.98      6933538.01
#Sta/Elev= 30
  4836.2 1655.59  4838.8 1655.59  4846.8 1652.59  4857.3 1649.87  4867.8 1649.06
  4888.9 1648.56  4910.0 1647.41  4920.5 1646.23  4941.6 1641.79  4952.2 1640.11
  4962.7 1639.18  4969.2 1639.14  4969.7 1638.64  4976.8 1638.64  4977.3 1639.14
  4983.8 1639.67  4997.4 1639.63  5007.9 1641.07  5030.8 1642.43  5037.0 1643.51
  5051.6 1644.02  5066.2 1645.96  5080.8 1649.03  5101.6 1649.25  5122.4 1651.27
  5137.0 1650.35  5166.2 1651.08  5172.4 1651.75  5194.3 1652.25  5244.3 1655.04
#Mann=3,-1,0
  4836.2    0.05       0  4969.2    0.05       0  4977.3    0.05       0
Bank Sta=4969.2,4977.3
Exp/Cntr=0.3,0.1

Type RM Length L Ch R = 1,11516,194,194,194
BEGIN DESCRIPTION:
Deadman 06 24.0
END DESCRIPTION:
XS GIS Cut Line= 3
      1598704.96      6933887.99      1599005.00      6933988.00
      1599480.04      6933912.99
#Sta/Elev= 30
  4682.7 1663.46  4693.3 1664.24  4714.4 1658.15  4735.4 1653.16  4746.0 1652.12
  4767.1 1651.29  4798.7 1651.98  4819.8 1654.09  4830.3 1656.26  4851.4 1658.99
  4861.9 1659.41  4872.5 1658.76  4893.6 1654.55  4935.7 1649.99  4967.3 1647.92
  4992.3 1647.19  4992.8 1646.69  4999.9 1646.69  5000.4 1647.19  5049.6 1648.18
  5090.1 1648.07  5140.7 1649.72  5157.6 1649.46  5282.4 1655.14  5292.6 1655.96
  5312.8 1656.24  5343.2 1657.53  5424.2 1657.51  5434.3 1658.16  5479.9 1657.66
#Mann=3,-1,0
  4682.7    0.05       0  4992.3    0.05       0  5000.4    0.05       0
Bank Sta=4992.3,5000.4
Exp/Cntr=0.3,0.1