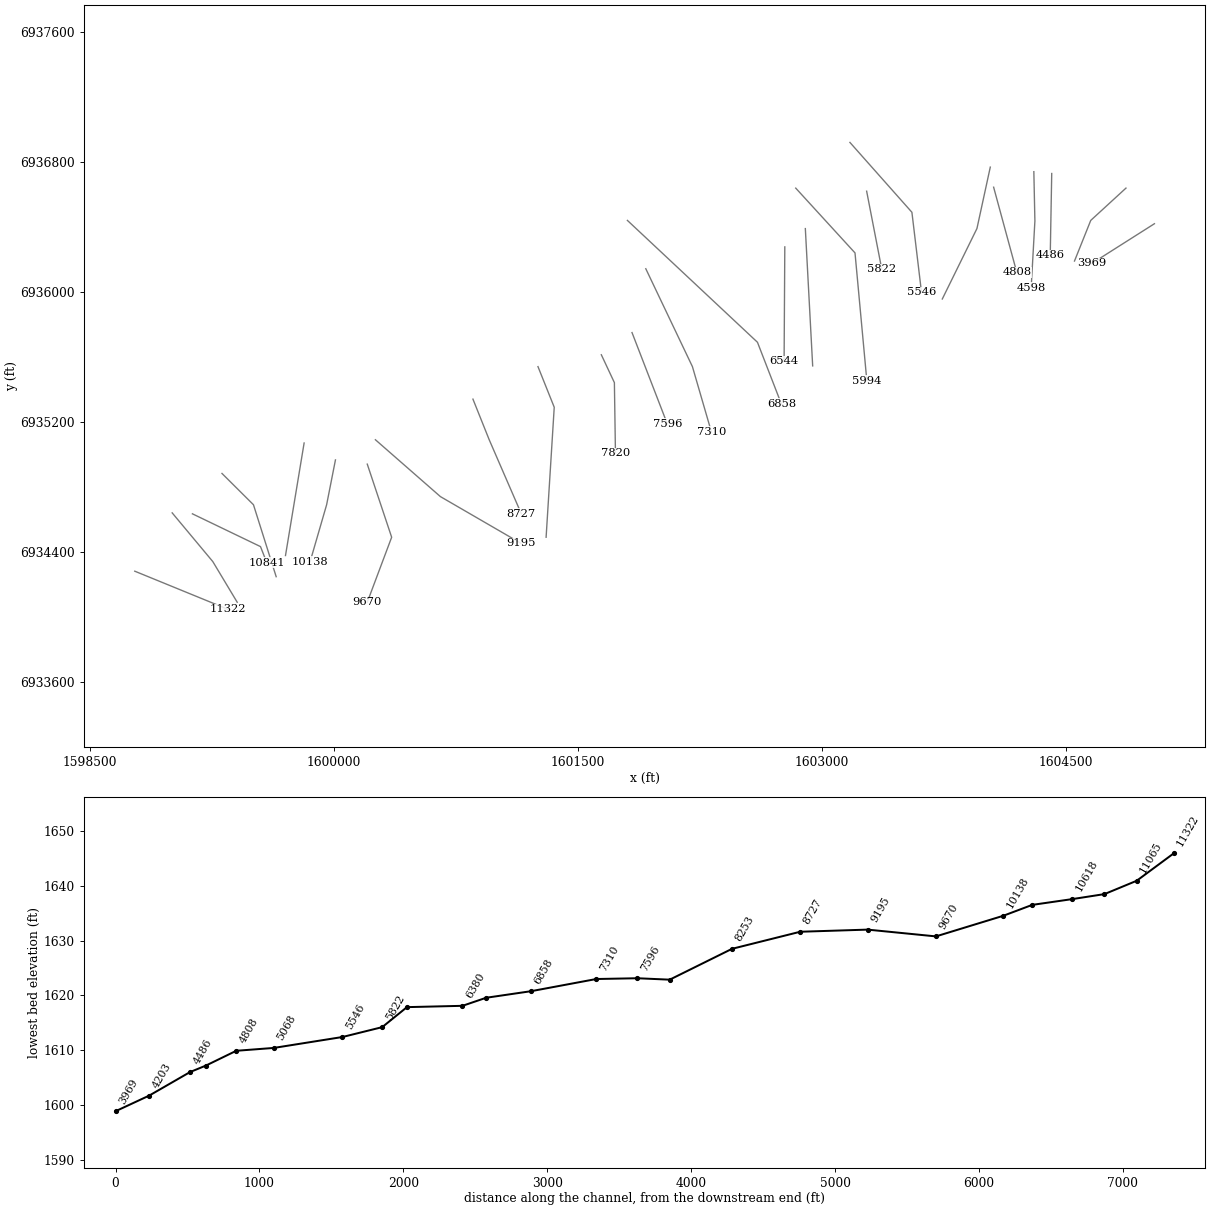
HEC-RAS study Deadman 06.prj: Deadman 06 Base Level Engineering

--- Deadman 06.g01 (geometry) --- (continued)

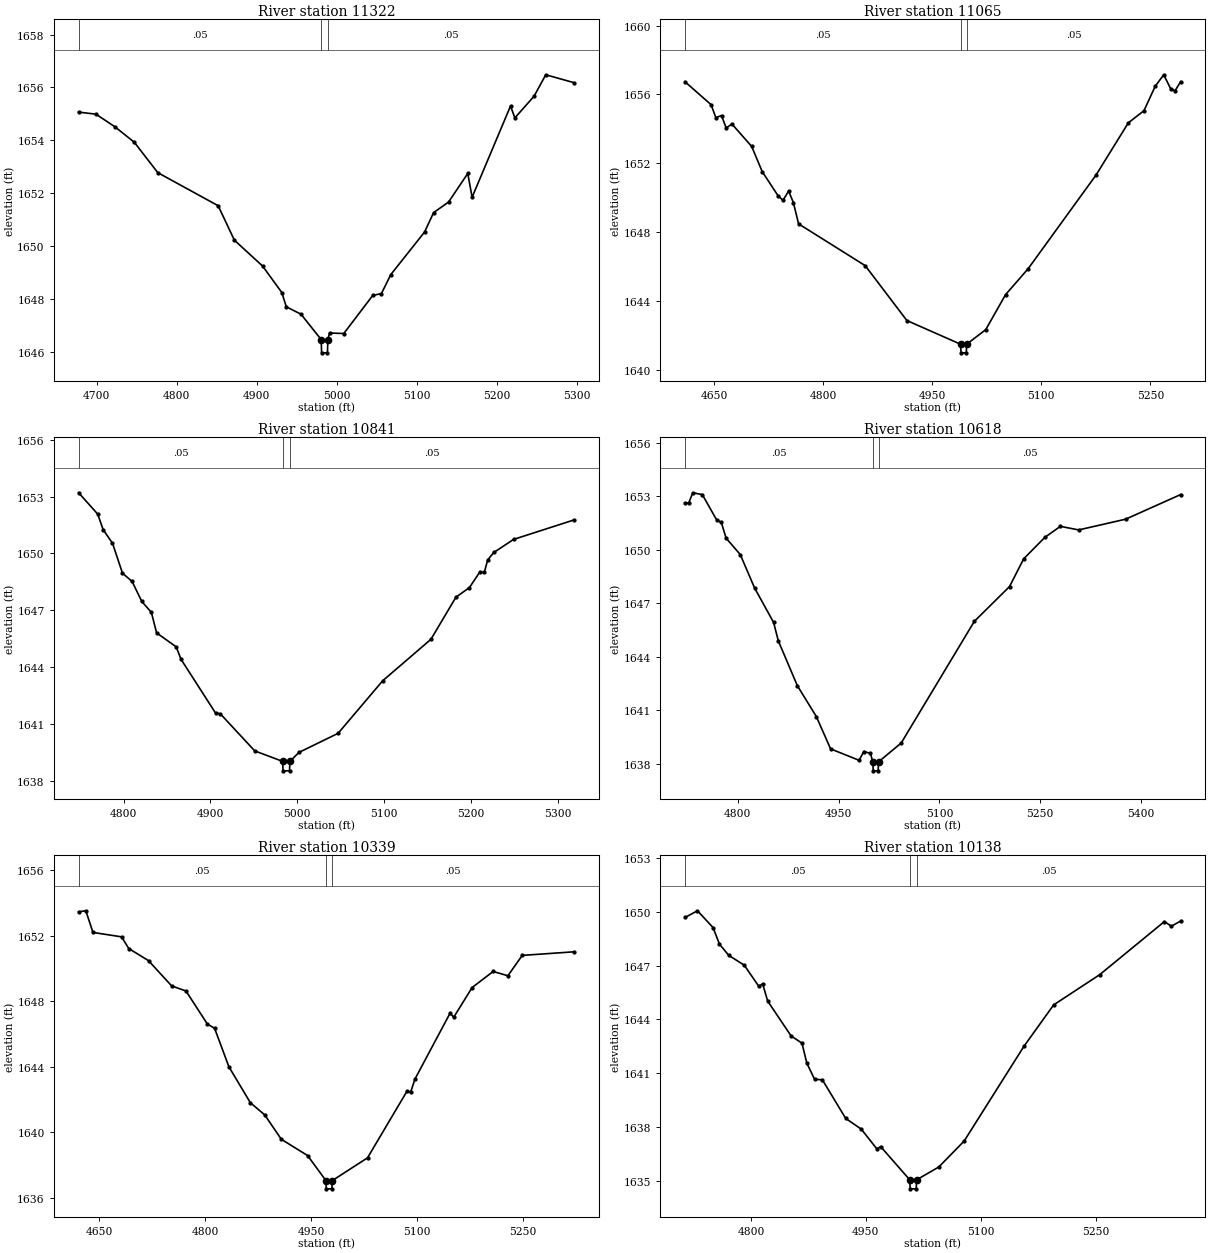
Type RM Length L Ch R = 1,11322,257,257,257
BEGIN DESCRIPTION:
Mapping XS c8f53b21
END DESCRIPTION:
XS GIS Cut Line= 2
      1598774.96      6934279.01      1599347.87      6934044.64
#Sta/Elev= 30
  4677.6 1655.07  4699.3 1654.99  4723.1 1654.51  4747.1 1653.93  4776.5 1652.78
  4851.9 1651.53  4872.1 1650.23  4907.4 1649.25  4931.4 1648.25  4937.0 1647.71
  4955.4 1647.43  4980.6 1646.47  4981.1 1645.97  4988.4 1645.97  4988.9 1646.47
  4991.0 1646.72  5008.8 1646.70  5045.0 1648.14  5055.8 1648.21  5067.6 1648.93
  5109.8 1650.54  5121.0 1651.27  5139.7 1651.67  5163.7 1652.75  5169.1 1651.85
  5217.1 1655.30  5222.5 1654.85  5246.5 1655.67  5261.1 1656.48  5296.6 1656.18
#Mann=3,-1,0
  4677.6    0.05       0  4980.6   0.035       0  4988.9    0.05       0
Bank Sta=4980.6,4988.9
Exp/Cntr=0.3,0.1

Type RM Length L Ch R = 1,11065,224,224,224
BEGIN DESCRIPTION:
Deadman 06 23.0
END DESCRIPTION:
XS GIS Cut Line= 3
      1599005.02      6934637.98      1599255.00      6934338.00
      1599404.98      6934088.03
#Sta/Elev= 30
  4609.7 1656.73  4645.5 1655.40  4652.0 1654.65  4659.8 1654.77  4666.3 1654.04
  4674.1 1654.28  4701.4 1652.97  4715.8 1651.51  4737.9 1650.09  4744.4 1649.84
  4752.2 1650.38  4758.7 1649.71  4765.9 1648.47  4857.6 1646.04  4914.9 1642.85
  4988.9 1641.47  4989.4 1640.97  4996.7 1640.97  4997.2 1641.47  5023.5 1642.32
  5050.7 1644.35  5081.8 1645.86  5175.1 1651.30  5219.8 1654.35  5241.2 1655.05
  5256.7 1656.47  5268.4 1657.14  5278.1 1656.32  5284.0 1656.21  5291.7 1656.74
#Mann=3,-1,0
  4609.7    0.05       0  4988.9   0.035       0  4997.2    0.05       0
Bank Sta=4988.9,4997.2
Exp/Cntr=0.3,0.1

Type RM Length L Ch R = 1,10841,223,223,223
BEGIN DESCRIPTION:
Mapping XS d993e5b9
END DESCRIPTION:
XS GIS Cut Line= 3
      1599129.47      6934632.16      1599548.28      6934430.35
      1599586.87      6934331.73
#Sta/Elev= 30
  4748.2 1653.20  4770.1 1652.08  4776.5 1651.25  4787.2 1650.54  4798.7 1648.96
  4809.8 1648.52  4820.9 1647.47  4832.0 1646.89  4838.0 1645.81  4860.6 1645.07
  4866.2 1644.41  4905.9 1641.58  4911.4 1641.54  4951.1 1639.58  4983.2 1639.03
  4983.7 1638.53  4991.1 1638.53  4991.6 1639.03  5001.9 1639.50  5047.1 1640.51
  5098.4 1643.28  5154.0 1645.47  5182.8 1647.69  5198.4 1648.20  5210.0 1649.00
  5215.5 1649.00  5219.4 1649.66  5226.4 1650.05  5249.2 1650.74  5319.0 1651.77
#Mann=3,-1,0
  4748.2    0.05       0  4983.2   0.035       0  4991.6    0.05       0
Bank Sta=4983.2,4991.6
Exp/Cntr=0.3,0.1

Type RM Length L Ch R = 1,10618,279,279,279
BEGIN DESCRIPTION:
Deadman 06 22.0
END DESCRIPTION:
XS GIS Cut Line= 3
      1599311.40      6934880.57      1599505.00      6934688.00
      1599644.71      6934245.18
#Sta/Elev= 30
  4721.5 1652.62  4726.9 1652.62  4732.9 1653.19  4747.1 1653.09  4768.3 1651.68
  4775.4 1651.53  4782.5 1650.65  4803.6 1649.73  4824.9 1647.86  4853.2 1645.93
  4860.2 1644.90  4888.5 1642.39  4916.8 1640.66  4938.0 1638.85  4980.4 1638.21
  4987.5 1638.70  4997.2 1638.60  5000.9 1638.12  5001.4 1637.62  5008.8 1637.62
  5009.3 1638.12  5043.1 1639.18  5151.9 1645.99  5204.3 1647.94  5225.3 1649.49
  5256.7 1650.69  5280.0 1651.31  5307.1 1651.11  5377.0 1651.71  5458.9 1653.09
#Mann=3,-1,0
  4721.5    0.05       0  5000.9   0.035       0  5009.3    0.05       0
Bank Sta=5000.9,5009.3
Exp/Cntr=0.3,0.1

Type RM Length L Ch R = 1,10339,201,201,201
BEGIN DESCRIPTION:
Mapping XS dfd8bdbb
END DESCRIPTION:
XS GIS Cut Line= 2
      1599816.58      6935068.07      1599702.00      6934375.38
#Sta/Elev= 30
  4620.6 1653.45  4630.8 1653.51  4640.9 1652.19  4681.5 1651.92  4691.6 1651.21
  4719.6 1650.47  4752.4 1648.93  4772.7 1648.62  4803.1 1646.60  4813.2 1646.35
  4833.5 1644.00  4863.9 1641.81  4884.2 1641.07  4907.8 1639.58  4945.0 1638.59
  4971.0 1637.06  4971.5 1636.56  4979.4 1636.56  4979.9 1637.06  5029.9 1638.45
  5085.8 1642.51  5090.9 1642.44  5097.1 1643.25  5146.9 1647.27  5152.0 1647.02
  5178.1 1648.83  5207.9 1649.81  5228.8 1649.55  5249.1 1650.79  5322.7 1651.01
#Mann=3,-1,0
  4620.6    0.05       0  4971.0   0.035       0  4979.9    0.05       0
Bank Sta=4971,4979.9
Exp/Cntr=0.3,0.1

Type RM Length L Ch R = 1,10138,468,468,468
BEGIN DESCRIPTION:
Deadman 06 21.0
END DESCRIPTION:
XS GIS Cut Line= 3
      1600009.28      6934963.88      1599955.00      6934688.00
      1599853.05      6934336.35
#Sta/Elev= 30
  4713.9 1649.68  4730.1 1650.05  4750.5 1649.11  4758.8 1648.19  4770.9 1647.57
  4791.2 1647.02  4810.1 1645.85  4815.2 1645.98  4821.8 1645.02  4852.4 1643.08
  4866.6 1642.68  4872.8 1641.58  4883.0 1640.67  4893.2 1640.64  4923.7 1638.49
  4944.1 1637.89  4964.3 1636.80  4969.4 1636.92  5007.4 1635.07  5007.9 1634.57
  5015.8 1634.57  5016.3 1635.07  5045.4 1635.79  5078.4 1637.23  5156.6 1642.51
  5195.3 1644.81  5255.4 1646.49  5340.0 1649.45  5349.1 1649.19  5361.2 1649.48
#Mann=3,-1,0
  4713.9    0.05       0  5007.4   0.035       0  5016.3    0.05       0
Bank Sta=5007.4,5016.3
Exp/Cntr=0.3,0.1

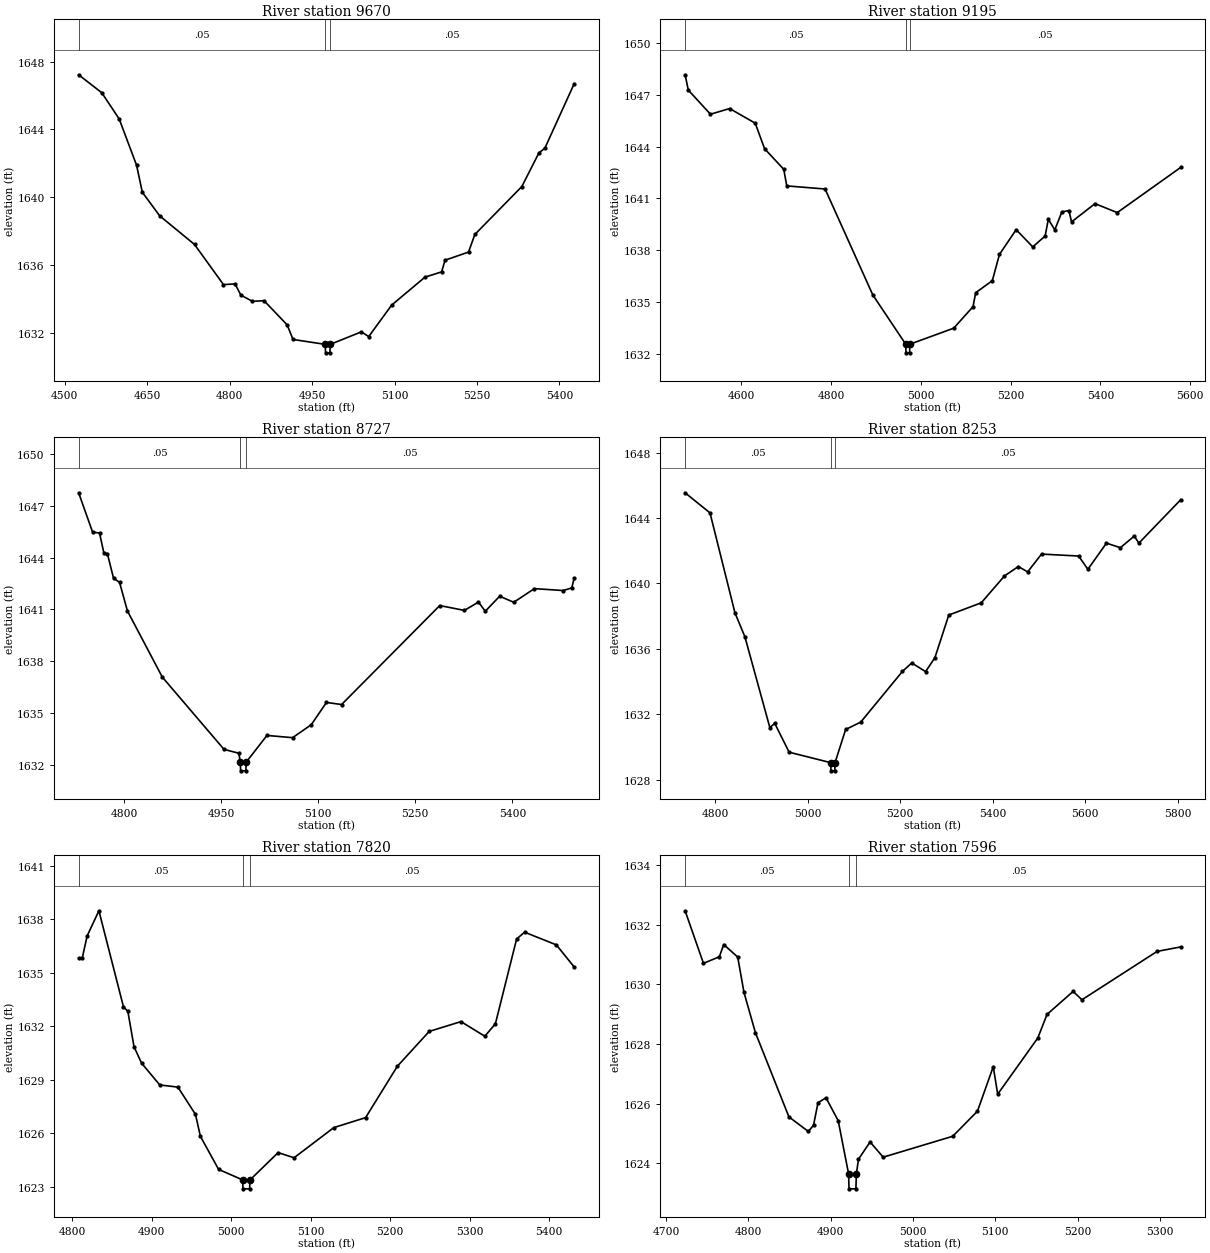
Type RM Length L Ch R = 1,9670,475,475,475
BEGIN DESCRIPTION:
Deadman 06 20.0
END DESCRIPTION:
XS GIS Cut Line= 3
      1600205.01      6934937.97      1600355.00      6934488.00
      1600205.00      6934088.01
#Sta/Elev= 30
  4525.2 1647.22  4567.3 1646.16  4599.0 1644.61  4630.6 1641.88  4641.1 1640.28
  4672.7 1638.89  4736.0 1637.20  4788.7 1634.83  4809.8 1634.87  4820.3 1634.21
  4841.4 1633.84  4862.5 1633.88  4904.6 1632.45  4915.2 1631.59  4973.9 1631.30
  4974.4 1630.80  4982.4 1630.80  4982.9 1631.30  5039.6 1632.04  5052.9 1631.76
  5094.7 1633.62  5155.3 1635.27  5185.5 1635.58  5191.8 1636.27  5234.5 1636.75
  5246.0 1637.79  5331.5 1640.62  5362.6 1642.61  5373.3 1642.88  5426.7 1646.69
#Mann=3,-1,0
  4525.2    0.05       0  4973.9    0.03       0  4982.9    0.05       0
Bank Sta=4973.9,4982.9
Exp/Cntr=0.3,0.1

Type RM Length L Ch R = 1,9195,468,468,468
BEGIN DESCRIPTION:
Deadman 06 19.0
END DESCRIPTION:
XS GIS Cut Line= 3
      1600254.97      6935088.03      1600655.00      6934738.00
      1601149.91      6934450.91
#Sta/Elev= 30
  4475.0 1648.18  4482.2 1647.29  4531.5 1645.89  4574.2 1646.22  4631.2 1645.37
  4652.0 1643.89  4694.8 1642.69  4701.4 1641.73  4786.8 1641.55  4893.1 1635.40
  4966.4 1632.54  4966.9 1632.04  4975.0 1632.04  4975.5 1632.54  5073.2 1633.47
  5116.3 1634.72  5122.2 1635.53  5159.3 1636.23  5175.1 1637.75  5212.3 1639.19
  5249.3 1638.19  5276.9 1638.82  5284.0 1639.79  5298.4 1639.18  5314.2 1640.22
  5329.9 1640.30  5335.7 1639.64  5388.0 1640.70  5437.5 1640.18  5578.7 1642.80
#Mann=3,-1,0
  4475.0    0.05       0  4966.4    0.03       0  4975.5    0.05       0
Bank Sta=4966.4,4975.5
Exp/Cntr=0.3,0.1

Type RM Length L Ch R = 1,8727,474,474,474
BEGIN DESCRIPTION:
Deadman 06 18.0
END DESCRIPTION:
XS GIS Cut Line= 3
      1600855.00      6935338.01      1600955.00      6935088.00
      1601152.61      6934632.27
#Sta/Elev= 30
  4729.6 1647.75  4751.2 1645.47  4761.9 1645.42  4768.7 1644.25  4774.0 1644.23
  4783.5 1642.81  4792.9 1642.56  4805.0 1640.91  4858.9 1637.08  4954.4 1632.89
  4977.3 1632.67  4979.5 1632.15  4980.0 1631.65  4988.1 1631.65  4988.6 1632.15
  5020.7 1633.70  5060.3 1633.57  5089.2 1634.32  5112.7 1635.61  5136.1 1635.49
  5287.8 1641.22  5325.9 1640.94  5347.7 1641.42  5358.2 1640.89  5380.4 1641.76
  5402.2 1641.41  5434.1 1642.20  5478.5 1642.09  5491.9 1642.24  5495.6 1642.81
#Mann=3,-1,0
  4729.6    0.05       0  4979.5    0.03       0  4988.6    0.05       0
Bank Sta=4979.5,4988.6
Exp/Cntr=0.3,0.1

Type RM Length L Ch R = 1,8253,433,433,433
BEGIN DESCRIPTION:
Deadman 06 17.0
END DESCRIPTION:
XS GIS Cut Line= 3
      1601255.01      6935537.98      1601355.00      6935288.00
      1601305.00      6934488.00
#Sta/Elev= 30
  4735.5 1645.54  4789.3 1644.31  4843.2 1638.20  4864.7 1636.73  4918.6 1631.18
  4929.3 1631.43  4960.3 1629.67  5050.2 1629.03  5050.7 1628.53  5059.0 1628.53
  5059.5 1629.03  5082.4 1631.06  5115.0 1631.51  5205.1 1634.61  5225.2 1635.13
  5255.2 1634.60  5275.3 1635.45  5305.3 1638.06  5375.5 1638.81  5425.6 1640.45
  5455.6 1641.03  5475.7 1640.70  5505.7 1641.79  5585.9 1641.67  5605.9 1640.86
  5646.0 1642.46  5676.0 1642.18  5706.1 1642.89  5716.1 1642.46  5806.3 1645.11
#Mann=3,-1,0
  4735.5    0.05       0  5050.2    0.05       0  5059.5    0.05       0
Bank Sta=5050.2,5059.5
Exp/Cntr=0.3,0.1

Type RM Length L Ch R = 1,7820,224,224,224
BEGIN DESCRIPTION:
Deadman 06 16.0
END DESCRIPTION:
XS GIS Cut Line= 3
      1601644.69      6935611.10      1601725.00      6935439.62
      1601731.51      6935005.63
#Sta/Elev= 30
  4807.9 1635.81  4812.4 1635.81  4818.6 1637.06  4833.4 1638.47  4864.3 1633.09
  4869.8 1632.84  4877.6 1630.85  4887.1 1629.93  4910.0 1628.71  4932.8 1628.59
  4954.9 1627.06  4961.1 1625.83  4984.0 1623.98  5014.2 1623.39  5014.7 1622.89
  5023.0 1622.89  5023.5 1623.39  5058.9 1624.92  5078.9 1624.63  5128.9 1626.32
  5168.9 1626.88  5208.9 1629.76  5248.9 1631.71  5288.9 1632.26  5318.9 1631.44
  5332.2 1632.14  5358.9 1636.89  5368.9 1637.27  5408.9 1636.56  5431.3 1635.32
#Mann=3,-1,0
  4807.9    0.05       0  5014.2    0.03       0  5023.5    0.05       0
Bank Sta=5014.2,5023.5
Exp/Cntr=0.3,0.1

Type RM Length L Ch R = 1,7596,286,286,286
BEGIN DESCRIPTION:
Mapping XS c701943f
END DESCRIPTION:
XS GIS Cut Line= 2
      1601833.43      6935747.63      1602050.23      6935186.13
#Sta/Elev= 30
  4723.3 1632.46  4745.6 1630.70  4764.9 1630.92  4770.2 1631.33  4787.2 1630.91
  4794.8 1629.73  4808.7 1628.38  4849.4 1625.56  4873.0 1625.07  4879.3 1625.28
  4884.7 1626.03  4894.4 1626.20  4909.3 1625.43  4921.9 1623.65  4922.4 1623.15
  4930.8 1623.15  4931.3 1623.65  4933.9 1624.14  4948.0 1624.72  4963.9 1624.21
  5048.4 1624.91  5078.4 1625.75  5097.6 1627.24  5103.0 1626.32  5151.7 1628.20
  5162.9 1628.99  5194.6 1629.76  5205.3 1629.48  5296.6 1631.10  5325.2 1631.25
#Mann=3,-1,0
  4723.3    0.05       0  4921.9    0.03       0  4931.3    0.05       0
Bank Sta=4921.9,4931.3
Exp/Cntr=0.3,0.1

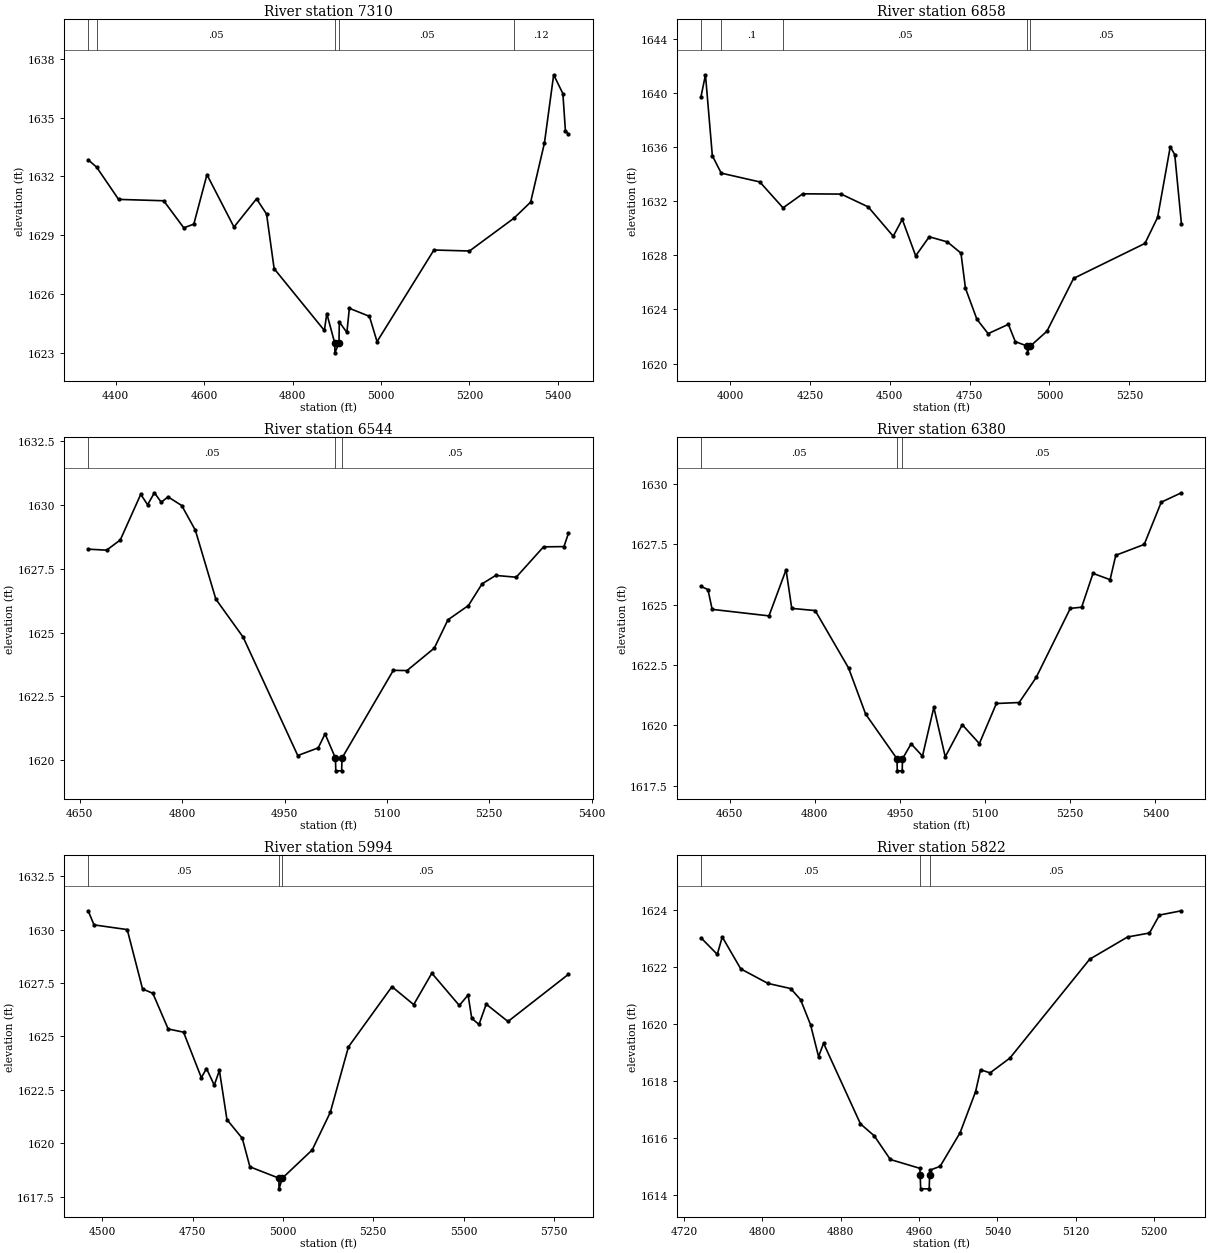
Type RM Length L Ch R = 1,7310,452,452,452
BEGIN DESCRIPTION:
Deadman 06 15.0
END DESCRIPTION:
XS GIS Cut Line= 3
      1601918.14      6936140.58      1602205.00      6935538.00
      1602321.79      6935135.79
#Sta/Elev= 30
  4337.8 1632.85  4357.1 1632.47  4406.7 1630.83  4508.7 1630.76  4554.1 1629.38
  4576.8 1629.57  4606.5 1632.09  4667.6 1629.42  4718.6 1630.86  4741.3 1630.08
  4758.4 1627.30  4872.0 1624.15  4877.5 1625.01  4895.4 1623.51  4895.9 1623.01
  4905.0 1623.51  4905.8 1624.58  4922.9 1624.05  4928.5 1625.28  4973.9 1624.87
  4991.1 1623.58  5119.7 1628.25  5200.1 1628.20  5300.6 1629.87  5338.4 1630.69
  5369.6 1633.70  5390.5 1637.18  5411.3 1636.22  5417.0 1634.34  5424.0 1634.14
#Mann=5,-1,0
  4337.8     0.1       0  4357.1    0.05       0  4895.4    0.05       0
  4905.0    0.05       0  5300.6    0.12       0
Bank Sta=4895.4,4905
Exp/Cntr=0.3,0.1

Type RM Length L Ch R = 1,6858,314,314,314
BEGIN DESCRIPTION:
Deadman 06 14.0
END DESCRIPTION:
XS GIS Cut Line= 3
      1601805.04      6936437.97      1602605.00      6935688.00
      1602751.90      6935308.58
#Sta/Elev= 30
  3909.5 1639.76  3923.4 1641.37  3944.9 1635.38  3972.7 1634.09  4093.4 1633.44
  4166.2 1631.52  4227.7 1632.56  4348.1 1632.54  4432.8 1631.59  4511.0 1629.42
  4539.3 1630.67  4581.3 1627.97  4623.8 1629.38  4680.5 1629.00  4723.0 1628.17
  4737.1 1625.57  4772.8 1623.28  4808.0 1622.21  4871.5 1622.90  4893.0 1621.62
  4930.6 1621.29  4931.1 1620.79  4940.2 1621.29  4992.1 1622.39  5075.5 1626.30
  5298.9 1628.89  5338.5 1630.82  5378.0 1636.04  5392.1 1635.46  5412.9 1630.36
#Mann=5,-1,0
  3909.5    0.05       0  3972.7     0.1       0  4166.2    0.05       0
  4930.6    0.03       0  4940.2    0.05       0
Bank Sta=4930.6,4940.2
Exp/Cntr=0.3,0.1

Type RM Length L Ch R = 1,6544,164,164,164
BEGIN DESCRIPTION:
Mapping XS 6f288aff
END DESCRIPTION:
XS GIS Cut Line= 2
      1602773.18      6936275.09      1602768.85      6935571.40
#Sta/Elev= 30
  4662.3 1628.27  4689.4 1628.23  4709.4 1628.63  4739.4 1630.42  4749.4 1630.01
  4759.4 1630.48  4769.4 1630.11  4779.4 1630.32  4799.4 1629.98  4819.4 1629.01
  4849.4 1626.31  4889.4 1624.82  4969.4 1620.18  4999.4 1620.48  5009.4 1621.03
  5024.6 1620.08  5025.1 1619.58  5033.7 1619.58  5034.2 1620.08  5109.4 1623.52
  5129.4 1623.51  5169.4 1624.39  5189.4 1625.50  5219.4 1626.06  5239.4 1626.91
  5259.4 1627.24  5289.4 1627.17  5329.4 1628.36  5359.4 1628.37  5366.0 1628.90
#Mann=3,-1,0
  4662.3    0.05       0  5024.6    0.03       0  5034.2    0.05       0
Bank Sta=5024.6,5034.2
Exp/Cntr=0.3,0.1

Type RM Length L Ch R = 1,6380,386,386,386
BEGIN DESCRIPTION:
Mapping XS 78a96410
END DESCRIPTION:
XS GIS Cut Line= 2
      1602899.48      6936387.56      1602944.59      6935542.57
#Sta/Elev= 30
  4599.7 1625.75  4611.9 1625.62  4619.3 1624.80  4719.4 1624.53  4749.5 1626.44
  4759.5 1624.84  4800.8 1624.75  4859.6 1622.37  4889.7 1620.46  4944.9 1618.61
  4945.4 1618.11  4954.1 1618.11  4954.6 1618.61  4969.8 1619.23  4989.8 1618.72
  5009.8 1620.74  5029.9 1618.69  5059.9 1620.02  5090.0 1619.24  5120.0 1620.90
  5160.1 1620.94  5190.1 1621.98  5250.2 1624.84  5270.2 1624.89  5290.2 1626.29
  5320.3 1626.03  5330.3 1627.04  5380.4 1627.49  5410.4 1629.24  5445.9 1629.63
#Mann=3,-1,0
  4599.7    0.05       0  4944.9    0.05       0  4954.6    0.05       0
Bank Sta=4944.9,4954.6
Exp/Cntr=0.3,0.1

Type RM Length L Ch R = 1,5994,172,172,172
BEGIN DESCRIPTION:
Deadman 06 13.0
END DESCRIPTION:
XS GIS Cut Line= 3
      1602840.43      6936636.70      1603205.00      6936238.00
      1603277.77      6935451.11
#Sta/Elev= 30
  4460.3 1630.88  4476.7 1630.22  4568.6 1630.00  4611.1 1627.22  4639.5 1627.02
  4682.0 1625.35  4724.6 1625.20  4773.9 1623.07  4788.1 1623.50  4809.7 1622.72
  4823.9 1623.41  4844.8 1621.11  4887.4 1620.23  4908.4 1618.90  4988.6 1618.37
  4989.1 1617.87  4998.3 1618.37  5080.9 1619.69  5131.1 1621.45  5181.3 1624.51
  5301.8 1627.33  5362.1 1626.49  5412.3 1627.96  5488.4 1626.45  5512.7 1626.94
  5522.8 1625.85  5542.9 1625.56  5562.9 1626.51  5623.2 1625.70  5790.8 1627.91
#Mann=3,-1,0
  4460.3    0.05       0  4988.6    0.03       0  4998.3    0.05       0
Bank Sta=4988.6,4998.3
Exp/Cntr=0.3,0.1

Type RM Length L Ch R = 1,5822,276,276,276
BEGIN DESCRIPTION:
Mapping XS d016920a
END DESCRIPTION:
XS GIS Cut Line= 2
      1603276.57      6936617.88      1603369.90      6936136.03
#Sta/Elev= 30
  4737.2 1623.02  4753.8 1622.44  4758.9 1623.05  4777.8 1621.93  4805.6 1621.42
  4828.8 1621.24  4838.9 1620.85  4849.1 1619.97  4857.3 1618.85  4862.4 1619.32
  4900.1 1616.49  4914.2 1616.07  4930.6 1615.24  4960.8 1614.93  4961.1 1614.71
  4961.6 1614.21  4970.3 1614.21  4970.8 1614.71  4971.4 1614.87  4981.5 1615.00
  5001.9 1616.18  5017.7 1617.62  5022.8 1618.39  5032.5 1618.28  5052.8 1618.80
  5134.3 1622.27  5173.0 1623.05  5195.4 1623.19  5205.6 1623.82  5228.0 1623.97
#Mann=3,-1,0
  4737.2    0.05       0  4961.1    0.03       0  4970.8    0.05       0
Bank Sta=4961.1,4970.8
Exp/Cntr=0.3,0.1

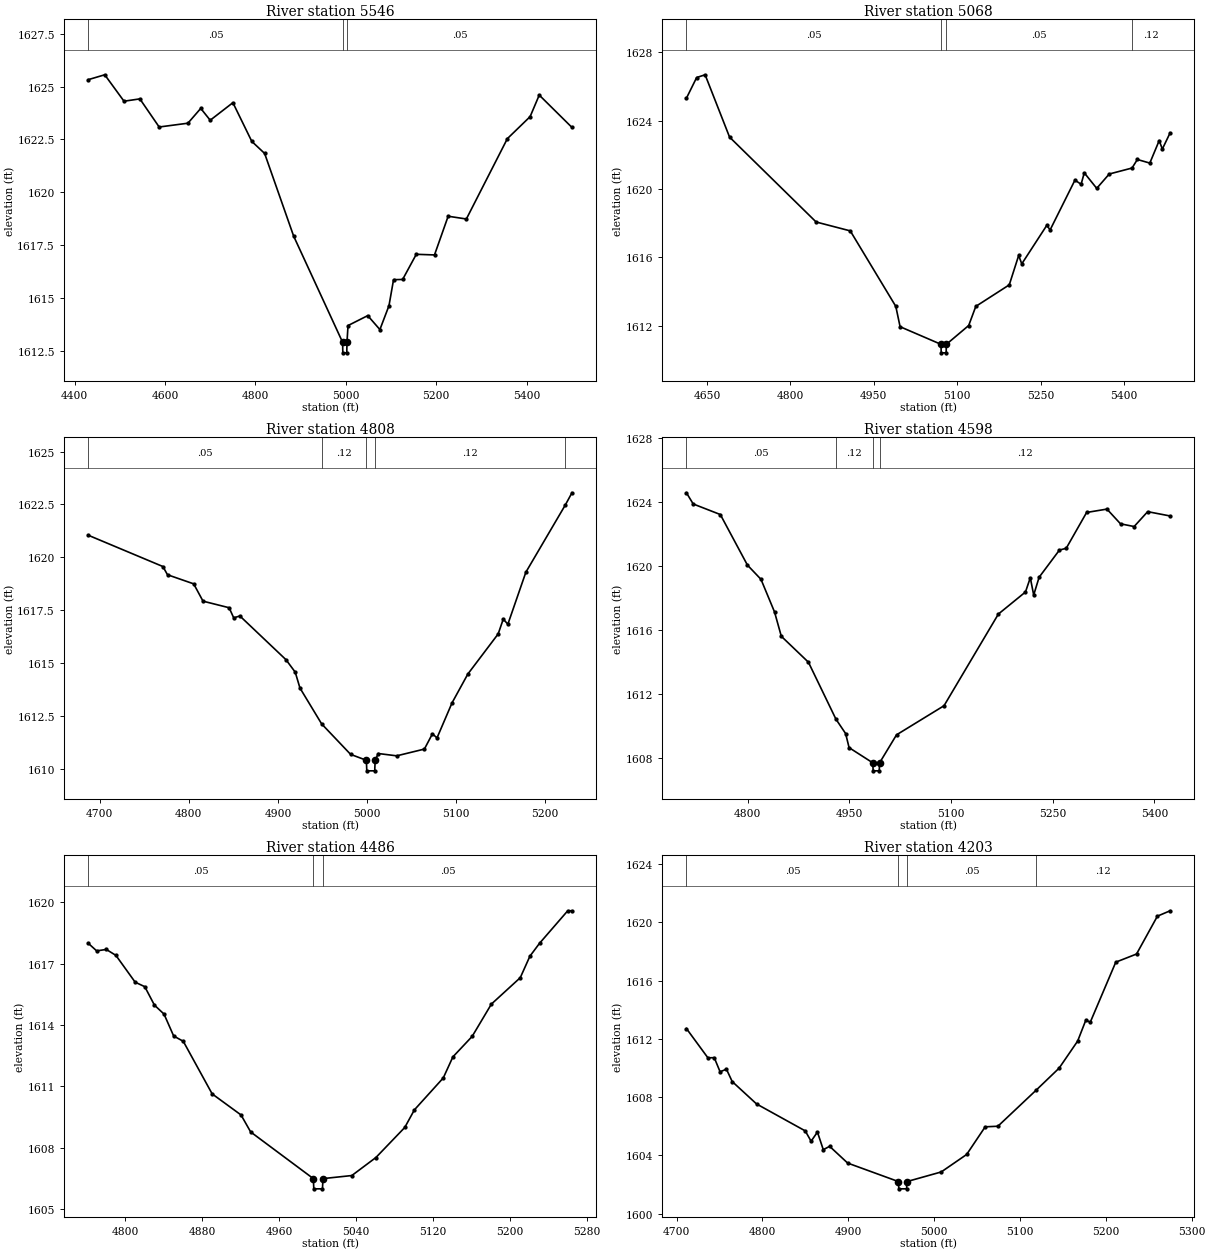
Type RM Length L Ch R = 1,5546,478,478,478
BEGIN DESCRIPTION:
Deadman 06 12.0
END DESCRIPTION:
XS GIS Cut Line= 3
      1603173.81      6936917.89      1603555.00      6936488.00
      1603613.89      6935996.07
#Sta/Elev= 30
  4430.2 1625.33  4466.6 1625.56  4509.2 1624.31  4544.3 1624.42  4587.0 1623.09
  4650.6 1623.27  4679.0 1623.97  4699.9 1623.41  4750.1 1624.24  4791.9 1622.41
  4820.3 1621.84  4884.5 1617.93  4992.8 1612.91  4993.3 1612.41  5002.0 1612.41
  5002.5 1612.91  5004.8 1613.70  5048.4 1614.17  5075.3 1613.51  5095.4 1614.64
  5105.5 1615.87  5125.6 1615.88  5155.8 1617.07  5196.1 1617.04  5226.3 1618.87
  5266.6 1618.74  5357.3 1622.54  5407.6 1623.58  5427.8 1624.60  5500.2 1623.07
#Mann=3,-1,0
  4430.2    0.05       0  4992.8    0.03       0  5002.5    0.05       0
Bank Sta=4992.8,5002.5
Exp/Cntr=0.3,0.1

Type RM Length L Ch R = 1,5068,260,260,260
BEGIN DESCRIPTION:
Deadman 06 11.0
END DESCRIPTION:
XS GIS Cut Line= 3
      1604037.07      6936766.02      1603955.00      6936388.00
      1603741.91      6935954.35
#Sta/Elev= 30
  4613.1 1625.32  4631.5 1626.53  4646.7 1626.69  4690.7 1623.04  4846.4 1618.07
  4907.8 1617.55  4989.7 1613.13  4997.4 1611.94  5070.9 1610.91  5071.4 1610.41
  5080.2 1610.41  5080.7 1610.91  5120.8 1612.01  5133.6 1613.13  5193.8 1614.39
  5210.7 1616.11  5216.3 1615.62  5261.2 1617.87  5267.3 1617.61  5311.9 1620.52
  5323.0 1620.28  5328.7 1620.95  5351.1 1620.04  5373.6 1620.88  5414.6 1621.23
  5424.2 1621.73  5446.6 1621.52  5463.5 1622.84  5469.1 1622.34  5483.1 1623.29
#Mann=4,-1,0
  4613.1    0.05       0  5070.9    0.03       0  5080.7    0.05       0
  5414.6    0.12       0
Bank Sta=5070.9,5080.7
Exp/Cntr=0.3,0.1

Type RM Length L Ch R = 1,4808,210,210,210
BEGIN DESCRIPTION:
Mapping XS 185bb4d6
END DESCRIPTION:
XS GIS Cut Line= 2
      1604057.64      6936642.38      1604200.10      6936117.99
#Sta/Elev= 30
  4687.0 1621.04  4770.8 1619.56  4776.0 1619.17  4805.4 1618.74  4815.9 1617.92
  4845.2 1617.61  4850.4 1617.13  4857.3 1617.22  4909.1 1615.15  4919.5 1614.56
  4924.8 1613.81  4949.2 1612.11  4981.7 1610.67  4999.4 1610.39  4999.9 1609.89
  5008.8 1609.89  5009.3 1610.39  5012.8 1610.71  5033.5 1610.60  5064.6 1610.92
  5073.6 1611.64  5078.8 1611.45  5095.7 1613.11  5113.4 1614.47  5147.5 1616.37
  5153.2 1617.07  5158.4 1616.83  5178.6 1619.29  5222.9 1622.47  5230.4 1623.05
#Mann=5,-1,0
  4687.0    0.05       0  4949.2    0.12       0  4999.4    0.07       0
  5009.3    0.12       0  5222.9    0.05       0
Bank Sta=4999.4,5009.3
Exp/Cntr=0.3,0.1

Type RM Length L Ch R = 1,4598,112,112,112
BEGIN DESCRIPTION:
Deadman 06 10.0
END DESCRIPTION:
XS GIS Cut Line= 3
      1604305.00      6936737.95      1604311.46      6936434.40
      1604288.63      6936024.96
#Sta/Elev= 30
  4709.6 1624.58  4719.6 1623.88  4759.6 1623.22  4799.6 1620.06  4819.6 1619.17
  4839.6 1617.13  4849.6 1615.61  4889.6 1613.99  4930.2 1610.43  4944.5 1609.53
  4949.6 1608.65  4984.6 1607.70  4985.1 1607.20  4994.1 1607.20  4994.6 1607.70
  5019.6 1609.45  5089.7 1611.27  5169.9 1617.00  5209.9 1618.38  5217.0 1619.27
  5222.0 1618.19  5230.0 1619.30  5260.0 1621.00  5270.0 1621.11  5300.1 1623.35
  5330.1 1623.56  5350.1 1622.64  5370.2 1622.47  5390.2 1623.40  5423.3 1623.13
#Mann=4,-1,0
  4709.6    0.05       0  4930.2    0.12       0  4984.6    0.07       0
  4994.6    0.12       0
Bank Sta=4984.6,4994.6
Exp/Cntr=0.3,0.1

Type RM Length L Ch R = 1,4486,283,283,283
BEGIN DESCRIPTION:
Mapping XS 5e3ffa7f
END DESCRIPTION:
XS GIS Cut Line= 2
      1604414.98      6936726.72      1604405.84      6936224.30
#Sta/Elev= 30
  4761.7 1617.99  4770.4 1617.62  4780.4 1617.69  4790.4 1617.40  4810.4 1616.09
  4820.4 1615.87  4830.4 1614.97  4840.4 1614.53  4850.4 1613.46  4860.4 1613.20
  4890.4 1610.63  4920.4 1609.60  4930.4 1608.77  4995.5 1606.49  4996.0 1605.99
  5005.0 1605.99  5005.5 1606.49  5035.5 1606.64  5060.5 1607.52  5090.5 1608.99
  5100.5 1609.85  5130.5 1611.41  5140.5 1612.44  5160.5 1613.44  5180.5 1615.02
  5210.5 1616.31  5220.5 1617.36  5230.5 1617.99  5259.8 1619.58  5264.2 1619.58
#Mann=3,-1,0
  4761.7    0.05       0  4995.5    0.03       0  5005.5    0.05       0
Bank Sta=4995.5,5005.5
Exp/Cntr=0.3,0.1

Type RM Length L Ch R = 1,4203,234,234,234
BEGIN DESCRIPTION:
Deadman 06 9.0
END DESCRIPTION:
XS GIS Cut Line= 3
      1604871.68      6936636.88      1604655.00      6936438.00
      1604554.99      6936187.98
#Sta/Elev= 30
  4711.5 1612.71  4736.5 1610.70  4743.9 1610.71  4750.7 1609.74  4758.1 1609.92
  4764.8 1609.07  4793.2 1607.53  4849.9 1605.68  4856.7 1604.97  4864.1 1605.60
  4870.9 1604.39  4878.3 1604.62  4899.3 1603.47  4958.4 1602.20  4958.9 1601.70
  4967.9 1601.70  4968.4 1602.20  5008.3 1602.86  5037.9 1604.06  5059.5 1605.96
  5074.3 1606.00  5118.9 1608.48  5145.6 1609.99  5167.2 1611.85  5176.6 1613.27
  5182.0 1613.16  5211.6 1617.27  5235.8 1617.83  5260.1 1620.43  5274.9 1620.80
#Mann=4,-1,0
  4711.5    0.05       0  4958.4    0.05       0  4968.4    0.05       0
  5118.9    0.12       0
Bank Sta=4958.4,4968.4
Exp/Cntr=0.3,0.1

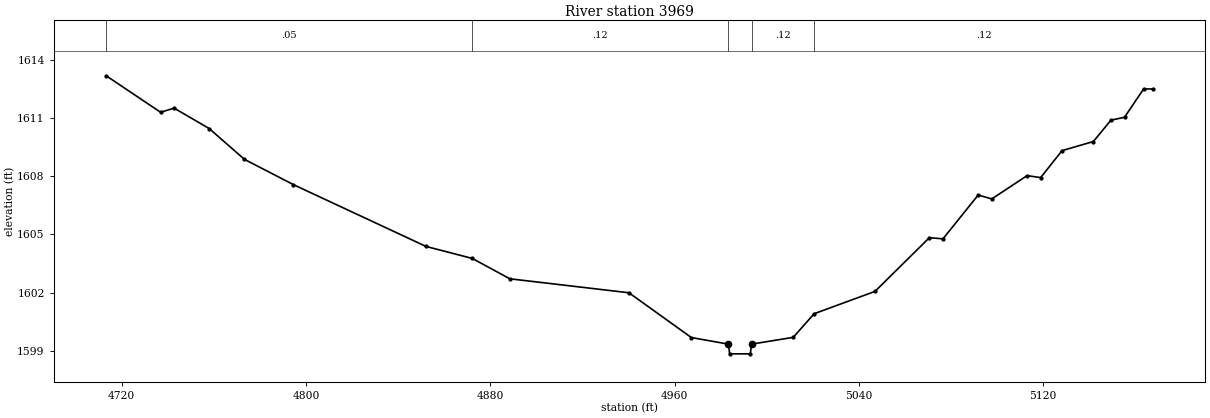
Type RM Length L Ch R = 1,3969,207,207,207
BEGIN DESCRIPTION:
Mapping XS a63daa73
END DESCRIPTION:
XS GIS Cut Line= 2
      1605046.71      6936417.66      1604663.10      6936174.09
#Sta/Elev= 30
  4713.3 1613.18  4736.9 1611.30  4742.8 1611.51  4758.0 1610.46  4773.3 1608.87
  4794.5 1607.57  4852.1 1604.38  4872.2 1603.76  4888.5 1602.71  4940.2 1601.99
  4967.3 1599.68  4983.4 1599.34  4983.9 1598.84  4992.9 1598.84  4993.4 1599.34
  5011.5 1599.69  5020.6 1600.91  5047.0 1602.06  5070.6 1604.83  5076.5 1604.77
  5091.8 1607.03  5097.7 1606.83  5113.0 1608.03  5118.9 1607.93  5128.2 1609.32
  5141.8 1609.79  5149.4 1610.89  5155.3 1611.04  5163.6 1612.50  5167.7 1612.50
#Mann=5,-1,0
  4713.3    0.05       0  4872.2    0.12       0  4983.4    0.05       0
  4993.4    0.12       0  5020.6    0.12       0
Bank Sta=4983.4,4993.4
Exp/Cntr=0.3,0.1