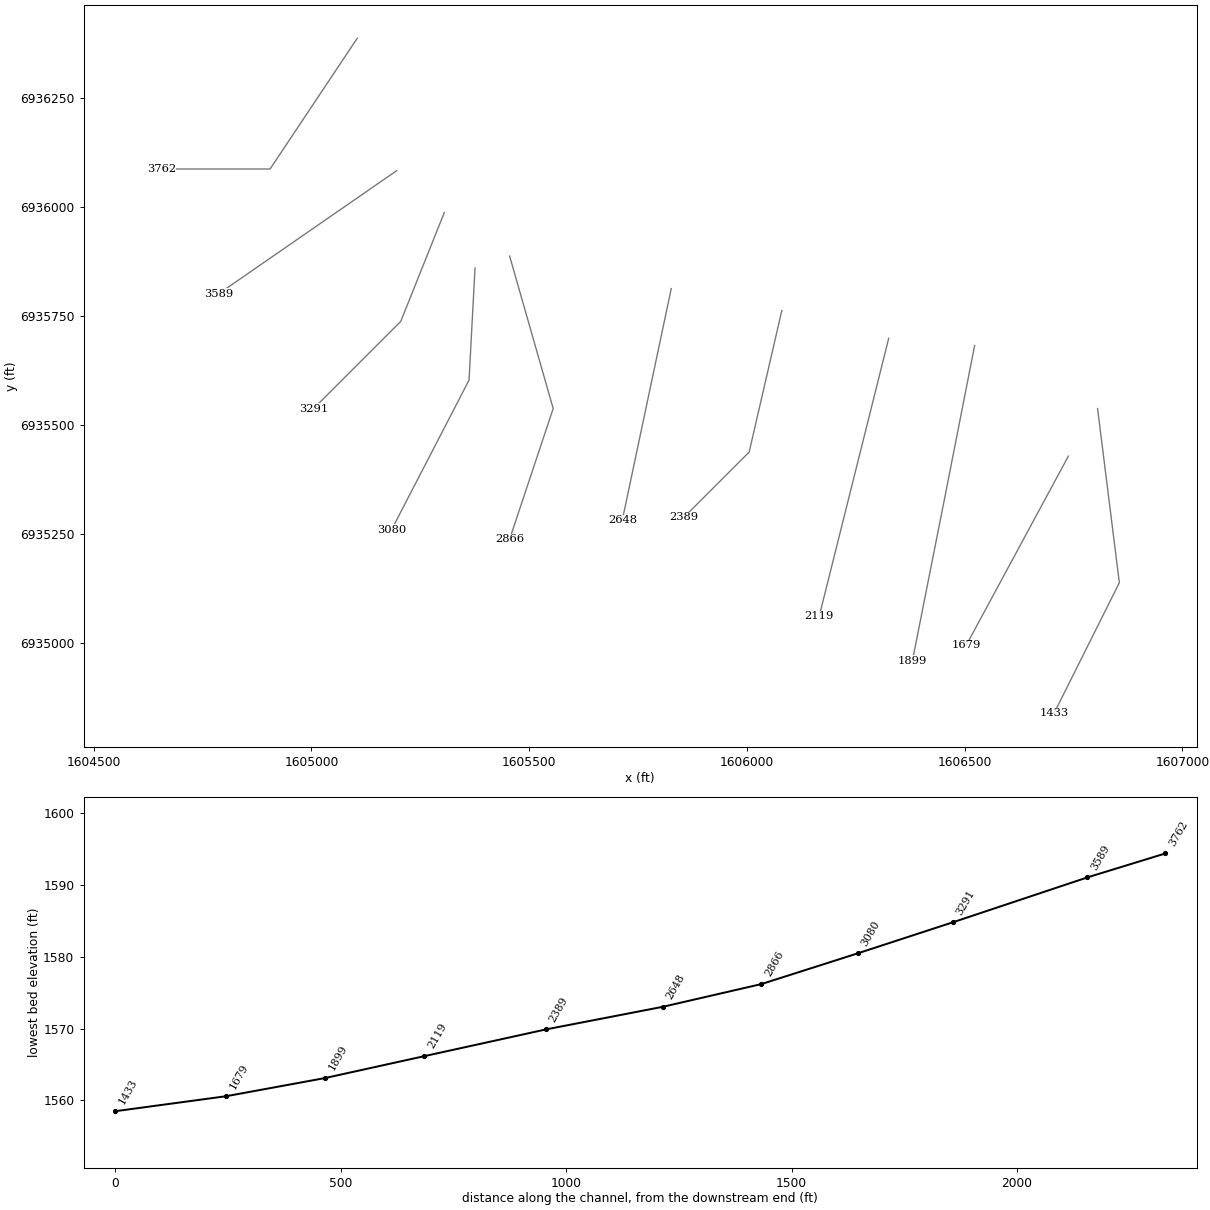
HEC-RAS study Deadman 06.prj: Deadman 06 Base Level Engineering

--- Deadman 06.g01 (geometry) --- (continued)

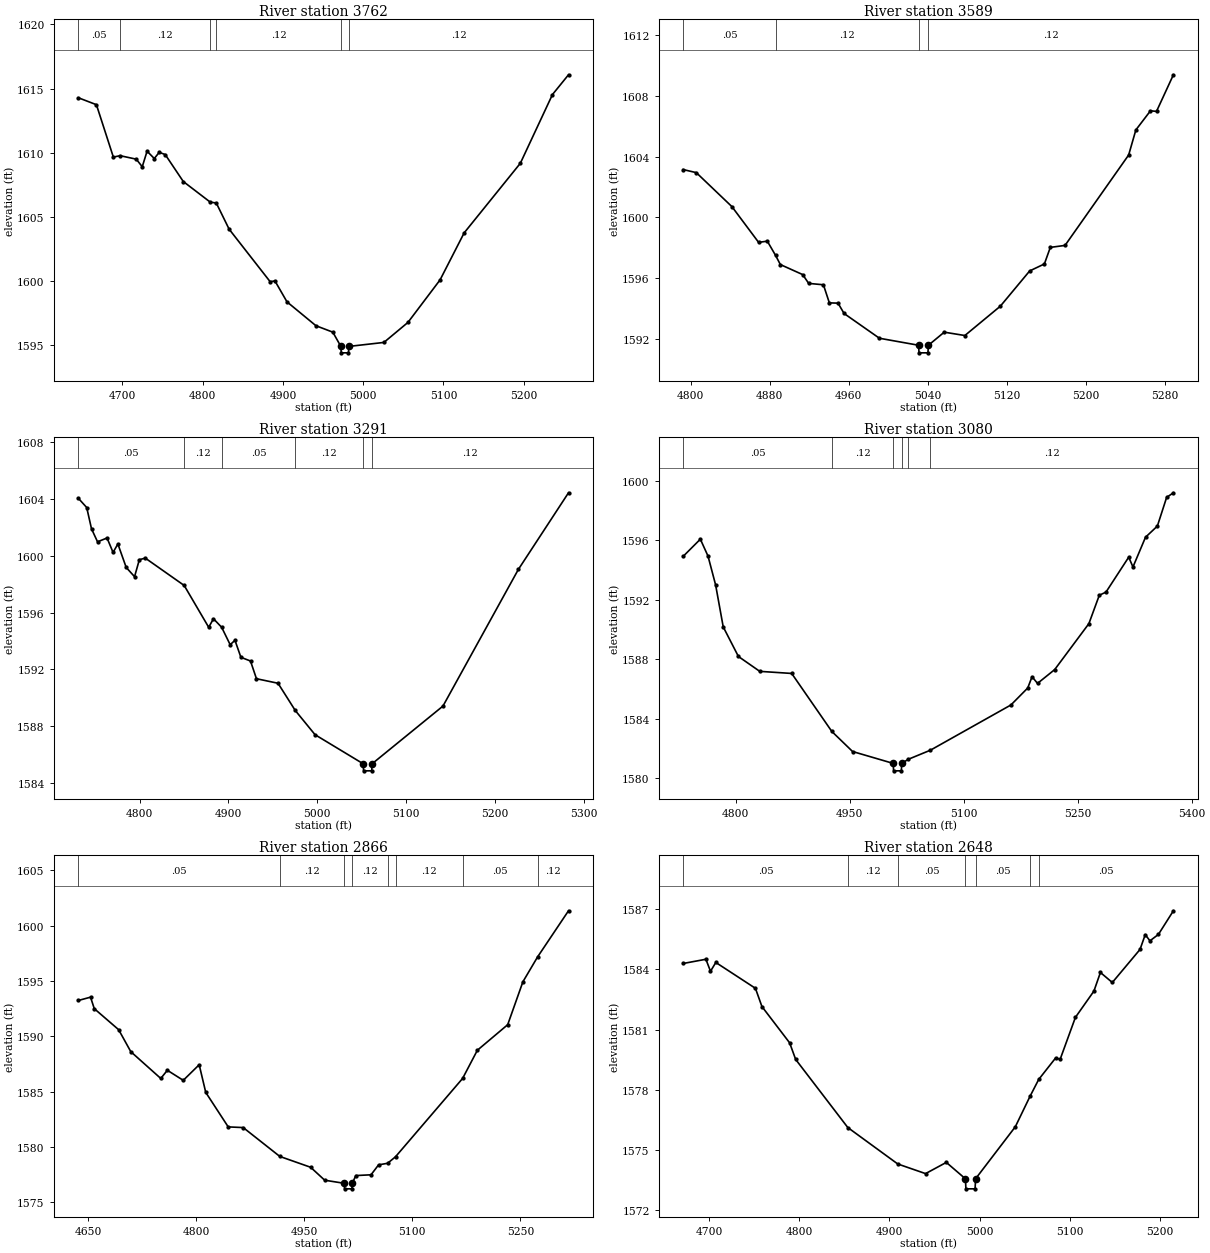
Type RM Length L Ch R = 1,3762,173,173,173
BEGIN DESCRIPTION:
Deadman 06 8.0
END DESCRIPTION:
XS GIS Cut Line= 3
      1605105.00      6936388.00      1604905.00      6936088.00
      1604654.96      6936088.00
#Sta/Elev= 30
  4645.2 1614.28  4667.7 1613.74  4688.8 1609.66  4697.2 1609.77  4717.3 1609.50
  4724.8 1608.91  4730.8 1610.12  4739.8 1609.55  4745.9 1610.03  4753.4 1609.86
  4775.9 1607.76  4809.6 1606.15  4817.0 1606.09  4833.0 1604.05  4884.1 1599.96
  4890.1 1600.02  4905.1 1598.39  4941.2 1596.53  4962.2 1596.03  4972.2 1594.92
  4972.7 1594.42  4981.7 1594.42  4982.2 1594.92  5025.8 1595.23  5055.8 1596.79
  5095.8 1600.10  5125.8 1603.76  5195.8 1609.18  5235.8 1614.53  5255.8 1616.07
#Mann=6,-1,0
  4645.2    0.05       0  4697.2    0.12       0  4809.6    0.05       0
  4817.0    0.12       0  4972.2    0.07       0  4982.2    0.12       0
Bank Sta=4972.2,4982.2
Exp/Cntr=0.3,0.1

Type RM Length L Ch R = 1,3589,298,298,298
BEGIN DESCRIPTION:
Mapping XS c4e3b2bd
END DESCRIPTION:
XS GIS Cut Line= 2
      1605195.85      6936084.26      1604787.71      6935802.05
#Sta/Elev= 30
  4792.5 1603.14  4805.7 1602.94  4841.8 1600.70  4868.8 1598.35  4877.6 1598.43
  4885.9 1597.50  4890.8 1596.89  4913.4 1596.23  4919.5 1595.65  4934.4 1595.56
  4940.4 1594.37  4949.2 1594.35  4955.3 1593.67  4991.1 1592.04  5030.7 1591.58
  5031.2 1591.08  5040.2 1591.08  5040.7 1591.58  5056.7 1592.44  5077.6 1592.22
  5113.5 1594.15  5143.2 1596.47  5158.1 1596.93  5164.1 1598.02  5179.0 1598.15
  5243.4 1604.10  5250.7 1605.75  5265.5 1607.01  5271.6 1606.97  5288.7 1609.38
#Mann=4,-1,0
  4792.5    0.05       0  4885.9    0.12       0  5030.7    0.07       0
  5040.7    0.12       0
Bank Sta=5030.7,5040.7
Exp/Cntr=0.3,0.1

Type RM Length L Ch R = 1,3291,211,211,211
BEGIN DESCRIPTION:
Deadman 06 7.0
END DESCRIPTION:
XS GIS Cut Line= 3
      1605305.01      6935988.02      1605205.00      6935738.00
      1605005.02      6935538.02
#Sta/Elev= 30
  4730.9 1604.06  4740.3 1603.41  4745.7 1601.91  4752.5 1600.99  4763.2 1601.26
  4770.0 1600.24  4775.4 1600.84  4784.8 1599.18  4794.2 1598.53  4799.6 1599.73
  4806.3 1599.84  4850.1 1597.91  4877.7 1594.96  4883.1 1595.56  4892.3 1594.96
  4901.9 1593.73  4907.3 1594.04  4914.0 1592.84  4924.8 1592.58  4931.5 1591.33
  4955.8 1591.01  4975.2 1589.09  4997.5 1587.38  5051.7 1585.33  5052.2 1584.83
  5061.3 1584.83  5061.8 1585.33  5141.6 1589.40  5226.5 1599.04  5283.0 1604.45
#Mann=6,-1,0
  4730.9    0.05       0  4850.1    0.12       0  4892.3    0.05       0
  4975.2    0.12       0  5051.7    0.07       0  5061.8    0.12       0
Bank Sta=5051.7,5061.8
Exp/Cntr=0.3,0.1

Type RM Length L Ch R = 1,3080,214,214,214
BEGIN DESCRIPTION:
Mapping XS 24f43af9
END DESCRIPTION:
XS GIS Cut Line= 3
      1605375.51      6935860.52      1605361.81      6935603.25
      1605183.72      6935259.25
#Sta/Elev= 30
  4730.9 1594.93  4753.4 1596.08  4763.5 1594.94  4773.5 1593.00  4783.5 1590.18
  4803.5 1588.19  4831.6 1587.19  4873.6 1587.05  4926.4 1583.15  4953.7 1581.80
  5007.2 1581.00  5007.7 1580.50  5017.9 1580.50  5018.4 1581.00  5027.2 1581.28
  5056.2 1581.89  5162.1 1584.93  5184.2 1586.07  5189.9 1586.83  5197.1 1586.38
  5219.7 1587.31  5264.7 1590.40  5278.4 1592.31  5287.2 1592.52  5317.1 1594.87
  5322.7 1594.21  5339.2 1596.21  5354.8 1596.96  5367.0 1598.89  5375.9 1599.20
#Mann=6,-1,0
  4730.9    0.05       0  4926.4    0.12       0  5007.2    0.07       0
  5018.4    0.12       0  5027.2    0.05       0  5056.2    0.12       0
Bank Sta=5007.2,5018.4
Exp/Cntr=0.3,0.1

Type RM Length L Ch R = 1,2866,218,218,218
BEGIN DESCRIPTION:
Deadman 06 6.0
END DESCRIPTION:
XS GIS Cut Line= 3
      1605454.99      6935888.03      1605555.00      6935538.00
      1605454.99      6935237.96
#Sta/Elev= 30
  4636.5 1593.24  4653.4 1593.54  4658.6 1592.50  4692.4 1590.60  4709.3 1588.61
  4750.9 1586.19  4760.0 1586.93  4782.1 1586.02  4804.2 1587.43  4813.3 1584.93
  4844.5 1581.81  4865.3 1581.75  4916.1 1579.14  4958.9 1578.16  4978.4 1576.99
  5005.5 1576.71  5006.0 1576.21  5016.2 1576.21  5016.7 1576.71  5021.6 1577.41
  5042.7 1577.48  5053.2 1578.38  5065.7 1578.52  5076.7 1579.11  5169.8 1586.19
  5190.3 1588.74  5232.4 1591.05  5253.5 1594.93  5273.9 1597.18  5316.8 1601.35
#Mann=8,-1,0
  4636.5    0.05       0  4916.1    0.12       0  5005.5    0.07       0
  5016.7    0.12       0  5065.7    0.05       0  5076.7    0.12       0
  5169.8    0.05       0  5273.9    0.12       0
Bank Sta=5005.5,5016.7
Exp/Cntr=0.3,0.1

Type RM Length L Ch R = 1,2648,259,259,259
BEGIN DESCRIPTION:
Mapping XS 4cff2f41
END DESCRIPTION:
XS GIS Cut Line= 2
      1605826.10      6935813.32      1605713.71      6935281.77
#Sta/Elev= 30
  4671.4 1584.30  4696.5 1584.51  4701.6 1583.91  4707.5 1584.35  4751.4 1583.06
  4758.6 1582.15  4789.3 1580.34  4796.0 1579.51  4853.8 1576.11  4909.2 1574.29
  4940.0 1573.81  4963.0 1574.37  4984.2 1573.55  4984.7 1573.05  4994.9 1573.05
  4995.4 1573.55  5039.5 1576.15  5055.8 1577.67  5065.4 1578.51  5084.1 1579.58
  5089.2 1579.52  5106.1 1581.61  5126.6 1582.92  5133.8 1583.85  5147.0 1583.35
  5177.7 1585.00  5183.5 1585.74  5188.7 1585.43  5198.1 1585.75  5214.7 1586.93
#Mann=7,-1,0
  4671.4    0.05       0  4853.8    0.12       0  4909.2    0.05       0
  4984.2    0.05       0  4995.4    0.05       0  5055.8    0.12       0
  5065.4    0.05       0
Bank Sta=4984.2,4995.4
Exp/Cntr=0.3,0.1

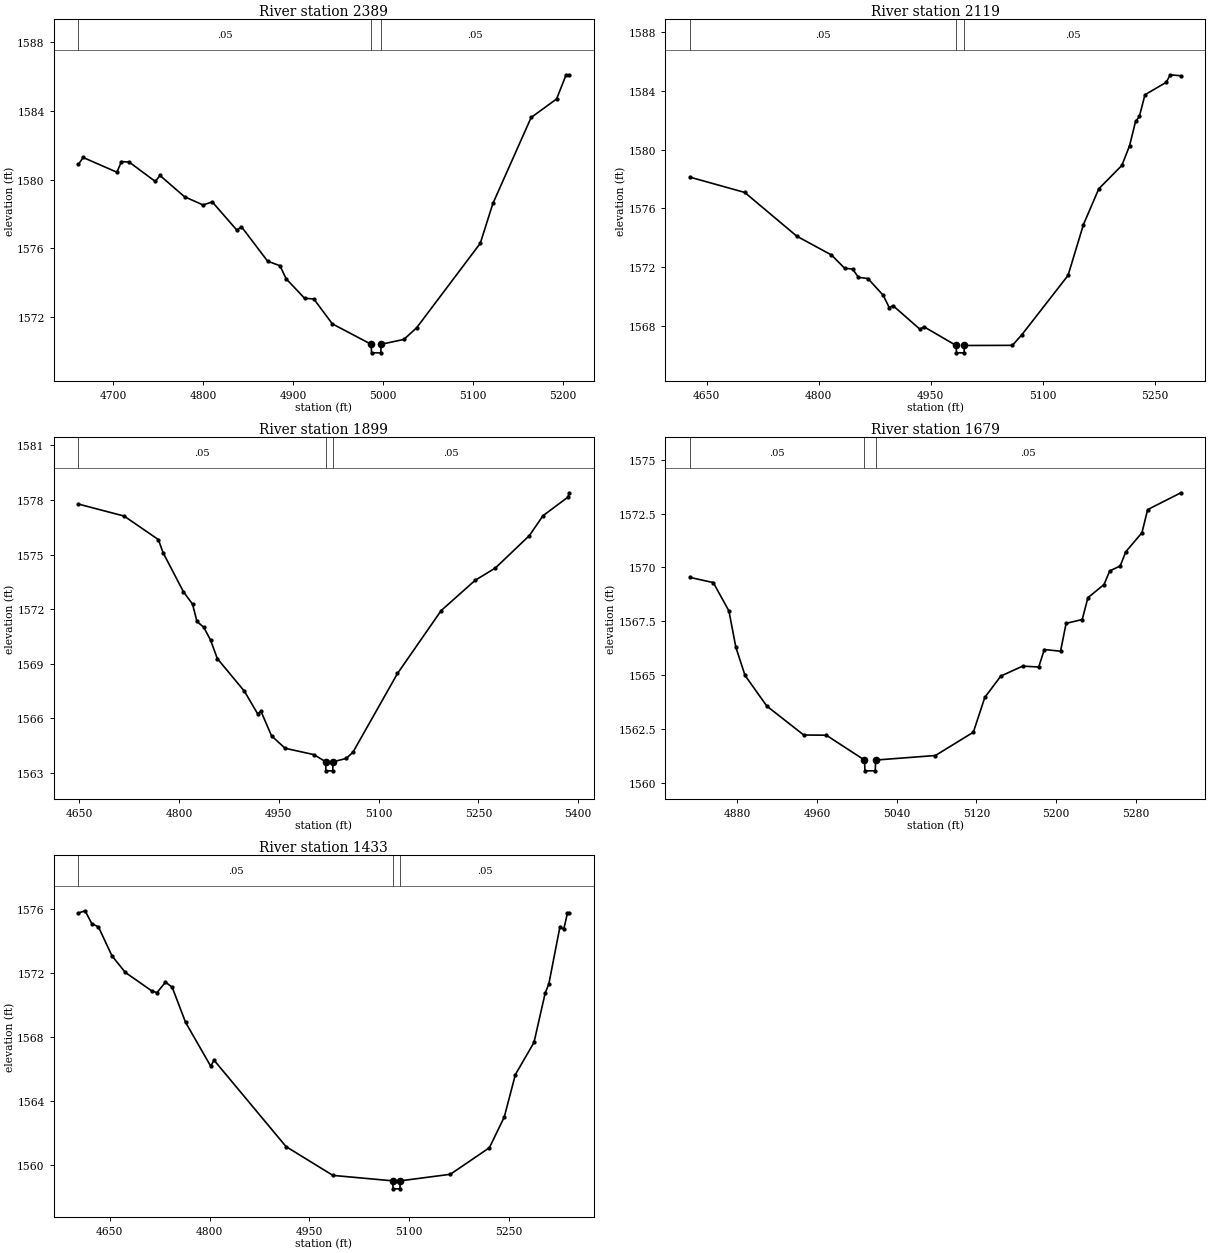
Type RM Length L Ch R = 1,2389,270,270,270
BEGIN DESCRIPTION:
Deadman 06 5.0
END DESCRIPTION:
XS GIS Cut Line= 3
      1606080.01      6935763.02      1606005.00      6935438.00
      1605855.00      6935288.00
#Sta/Elev= 30
  4661.3 1580.88  4666.5 1581.29  4704.1 1580.43  4709.2 1581.05  4717.8 1581.02
  4746.8 1579.89  4752.0 1580.24  4779.3 1579.00  4799.9 1578.52  4810.1 1578.70
  4837.5 1577.05  4842.6 1577.25  4871.7 1575.24  4885.4 1574.98  4892.2 1574.22
  4912.8 1573.08  4923.0 1573.04  4943.6 1571.59  4986.7 1570.40  4987.2 1569.90
  4997.4 1569.90  4997.9 1570.40  5023.1 1570.68  5037.3 1571.36  5108.0 1576.28
  5122.1 1578.61  5164.6 1583.62  5192.9 1584.70  5203.5 1586.11  5207.0 1586.11
#Mann=3,-1,0
  4661.3    0.05       0  4986.7    0.05       0  4997.9    0.05       0
Bank Sta=4986.7,4997.9
Exp/Cntr=0.3,0.1

Type RM Length L Ch R = 1,2119,220,220,220
BEGIN DESCRIPTION:
Mapping XS cfa1c78e
END DESCRIPTION:
XS GIS Cut Line= 2
      1606325.40      6935699.15      1606165.95      6935061.38
#Sta/Elev= 30
  4627.5 1578.13  4700.8 1577.09  4770.6 1574.11  4817.0 1572.83  4834.8 1571.92
  4845.2 1571.88  4853.1 1571.31  4865.8 1571.23  4886.4 1570.08  4894.3 1569.25
  4899.5 1569.38  4935.6 1567.77  4940.7 1567.95  4983.9 1566.67  4984.4 1566.17
  4994.6 1566.17  4995.1 1566.67  5059.3 1566.68  5071.9 1567.40  5133.8 1571.44
  5154.4 1574.90  5175.0 1577.34  5205.9 1578.93  5216.2 1580.27  5224.2 1581.92
  5229.3 1582.26  5236.8 1583.74  5265.4 1584.59  5270.6 1585.10  5284.9 1585.03
#Mann=3,-1,0
  4627.5    0.05       0  4983.9    0.05       0  4995.1    0.05       0
Bank Sta=4983.9,4995.1
Exp/Cntr=0.3,0.1

Type RM Length L Ch R = 1,1899,220,220,220
BEGIN DESCRIPTION:
Deadman 06 4.0
END DESCRIPTION:
XS GIS Cut Line= 3
      1606522.76      6935682.80      1606455.00      6935338.00
      1606379.96      6934959.26
#Sta/Elev= 30
  4649.0 1577.78  4717.7 1577.12  4769.1 1575.83  4776.2 1575.11  4806.8 1572.96
  4820.5 1572.28  4827.1 1571.33  4837.3 1571.01  4847.5 1570.31  4857.7 1569.29
  4898.5 1567.49  4918.2 1566.26  4923.3 1566.39  4939.2 1565.04  4959.6 1564.36
  5002.9 1564.01  5020.4 1563.62  5020.9 1563.12  5031.1 1563.12  5031.6 1563.62
  5051.4 1563.80  5061.6 1564.15  5128.4 1568.47  5194.1 1571.93  5245.1 1573.59
  5275.6 1574.27  5326.6 1576.05  5347.0 1577.14  5384.5 1578.16  5386.5 1578.40
#Mann=3,-1,0
  4649.0    0.05       0  5020.4    0.05       0  5031.6    0.05       0
Bank Sta=5020.4,5031.6
Exp/Cntr=0.3,0.1

Type RM Length L Ch R = 1,1679,246,246,246
BEGIN DESCRIPTION:
Mapping XS b3b9d9e8
END DESCRIPTION:
XS GIS Cut Line= 2
      1606737.93      6935428.59      1606503.59      6934994.62
#Sta/Elev= 30
  4832.3 1569.54  4855.7 1569.30  4871.4 1567.99  4878.4 1566.30  4887.6 1565.00
  4909.5 1563.58  4946.6 1562.24  4969.3 1562.23  5007.6 1561.08  5008.1 1560.58
  5018.4 1560.58  5018.9 1561.08  5078.9 1561.29  5117.0 1562.37  5128.5 1563.98
  5144.6 1564.97  5166.5 1565.43  5182.7 1565.39  5188.3 1566.20  5204.6 1566.12
  5210.2 1567.41  5226.4 1567.59  5232.1 1568.60  5248.3 1569.21  5254.0 1569.84
  5264.5 1570.07  5270.2 1570.73  5286.4 1571.61  5292.1 1572.68  5325.5 1573.46
#Mann=3,-1,0
  4832.3    0.05       0  5007.6   0.035       0  5018.9    0.05       0
Bank Sta=5007.6,5018.9
Exp/Cntr=0.3,0.1

Type RM Length L Ch R = 1,1433,0,0,0
BEGIN DESCRIPTION:
Deadman 06 3.0
END DESCRIPTION:
XS GIS Cut Line= 3
      1606805.00      6935537.98      1606855.00      6935138.00
      1606705.00      6934838.00
#Sta/Elev= 30
  4602.7 1575.73  4612.8 1575.87  4622.8 1575.07  4632.9 1574.86  4653.1 1573.06
  4673.2 1572.02  4713.5 1570.85  4721.1 1570.76  4733.7 1571.41  4743.8 1571.09
  4763.9 1568.90  4801.7 1566.16  4806.8 1566.53  4915.1 1561.13  4985.6 1559.33
  5075.6 1558.99  5076.1 1558.49  5086.4 1558.49  5086.9 1558.99  5162.3 1559.40
  5221.0 1561.06  5243.4 1562.98  5260.1 1565.63  5288.1 1567.64  5304.9 1570.72
  5310.5 1571.31  5327.2 1574.88  5332.8 1574.71  5338.4 1575.71  5341.2 1575.71
#Mann=3,-1,0
  4602.7    0.05       0  5075.6   0.035       0  5086.9    0.05       0
Bank Sta=5075.6,5086.9
Exp/Cntr=0.3,0.1

Chan Stop Cuts=-1