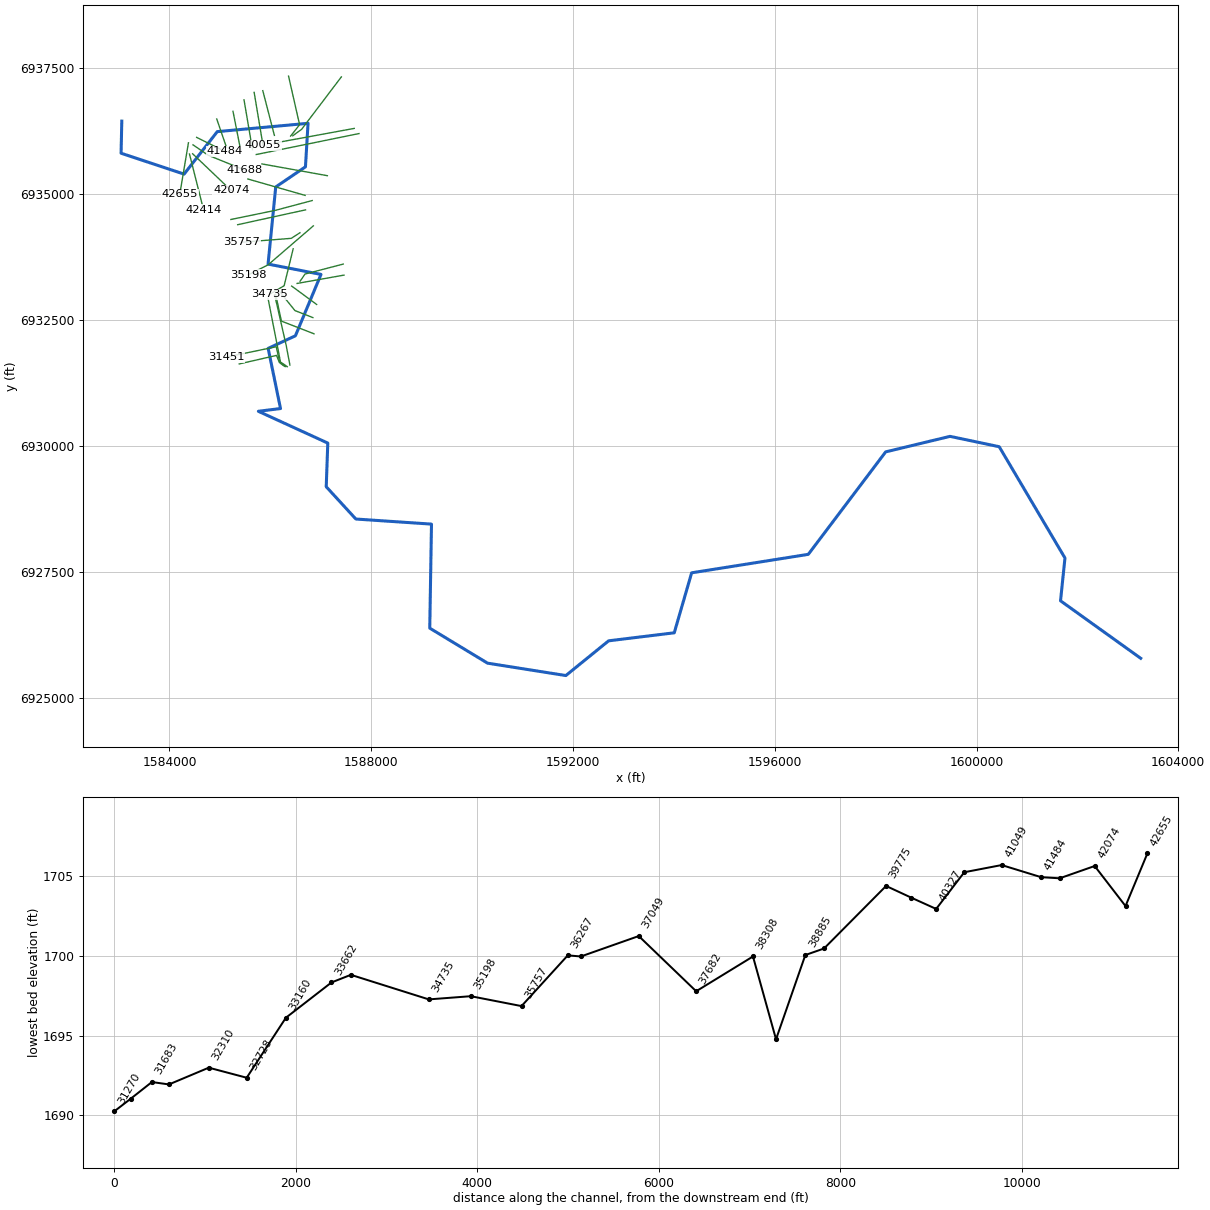
--- Deadman 07.prj (project) ---

Proj Title=Deadman 07 Base Level Engineering
Current Plan=p01
Default Exp/Contr=0.3,0.1
English Units
Geom File=g01
Flow File=f01
Plan File=p01
BEGIN DESCRIPTION:
Deadman 07
END DESCRIPTION:

--- Deadman 07.p01 (plan) ---

Plan Title=Multiple Run
Short Identifier=Multiple
Geom File=g01
Flow File=f01
Subcritical Flow
K Sum by GR= 0
Std Step Tol= 0.01
Critical Tol= 0.01
Num of Std Step Trials= 20
Max Error Tol= 0.3
Flow Tol Ratio= 0.001
Split Flow NTrial= 30
Split Flow Tol= 0.02
Split Flow Ratio= 0.02
Log Output Level= 0
Friction Slope Method= 1
Unsteady Friction Slope Method= 2
Unsteady Bridges Friction Slope Method= 1
Parabolic Critical Depth
Global Vel Dist=  1 , 1 , 1
Global Log Level= 0
CheckData=True
Encroach Param= -1, 0, 0, 0
BEGIN DESCRIPTION:
Multiple Run
END DESCRIPTION:

--- Deadman 07.f01 (steady flow) ---

Flow Title=Multiple
Number of Profiles=7
Profile Names=10-year,25-year,50-year,1pct_min,100-year,1pct_plu,500-year
River Rch & RM= Deadman 07,Reach-1,42655
     190     250     297     175     349     697     490
River Rch & RM= Deadman 07,Reach-1,36267
     227     302     360     214     426     850     604
River Rch & RM= Deadman 07,Reach-1,28118
     253     338     405     240     479     956     682
River Rch & RM= Deadman 07,Reach-1,21201
     278     373     447     266     531    1060     760
River Rch & RM= Deadman 07,Reach-1,19019
     446     613     747     452     901    1799    1329
River Rch & RM= Deadman 07,Reach-1,13830
     572     796     980     598    1193    2381    1792
River Rch & RM= Deadman 07,Reach-1,8601
     662     930    1154     709    1415    2823    2156
River Rch & RM= Deadman 07,Reach-1,2574
     716    1011    1258     776    1548    3088    2373
Boundary for River Rch & Prof#=Deadman 07,Reach-1,1
Up Type=0
Dn Type=3
Dn Slope=0.022
Boundary for River Rch & Prof#=Deadman 07,Reach-1,2
Up Type=0
Dn Type=3
Dn Slope=0.022
Boundary for River Rch & Prof#=Deadman 07,Reach-1,3
Up Type=0
Dn Type=3
Dn Slope=0.022
Boundary for River Rch & Prof#=Deadman 07,Reach-1,4
Up Type=0
Dn Type=3
Dn Slope=0.022
Boundary for River Rch & Prof#=Deadman 07,Reach-1,5
Up Type=0
Dn Type=3
Dn Slope=0.022
Boundary for River Rch & Prof#=Deadman 07,Reach-1,6
Up Type=0
Dn Type=3
Dn Slope=0.022
Boundary for River Rch & Prof#=Deadman 07,Reach-1,7
Up Type=0
Dn Type=3
Dn Slope=0.022

--- Deadman 07.g01 (geometry) ---

Geom Title=Existing Conditions

River Reach=Deadman 07,Reach-1
Reach XY= 30
      1583055.00      6936438.00      1583040.97      6935801.12
      1584289.92      6935387.21      1584948.05      6936229.15
      1586747.53      6936394.08      1586696.03      6935531.33
      1586106.87      6935132.31      1585955.01      6933603.36
      1587004.28      6933398.71      1586497.14      6932181.83
      1585956.61      6931931.98      1586201.63      6930739.22
      1585762.51      6930684.90      1587138.81      6930054.70
      1587108.08      6929189.21      1587694.95      6928549.11
      1589194.72      6928448.16      1589160.45      6926385.55
      1590306.46      6925691.54      1591858.32      6925446.04
      1592706.47      6926134.46      1594007.46      6926293.46
      1594352.45      6927482.78      1596664.68      6927848.76
      1598198.81      6929880.19      1599475.03      6930187.93
      1600449.53      6929982.89      1601753.36      6927776.17
      1601665.32      6926927.82      1603255.00      6925788.00

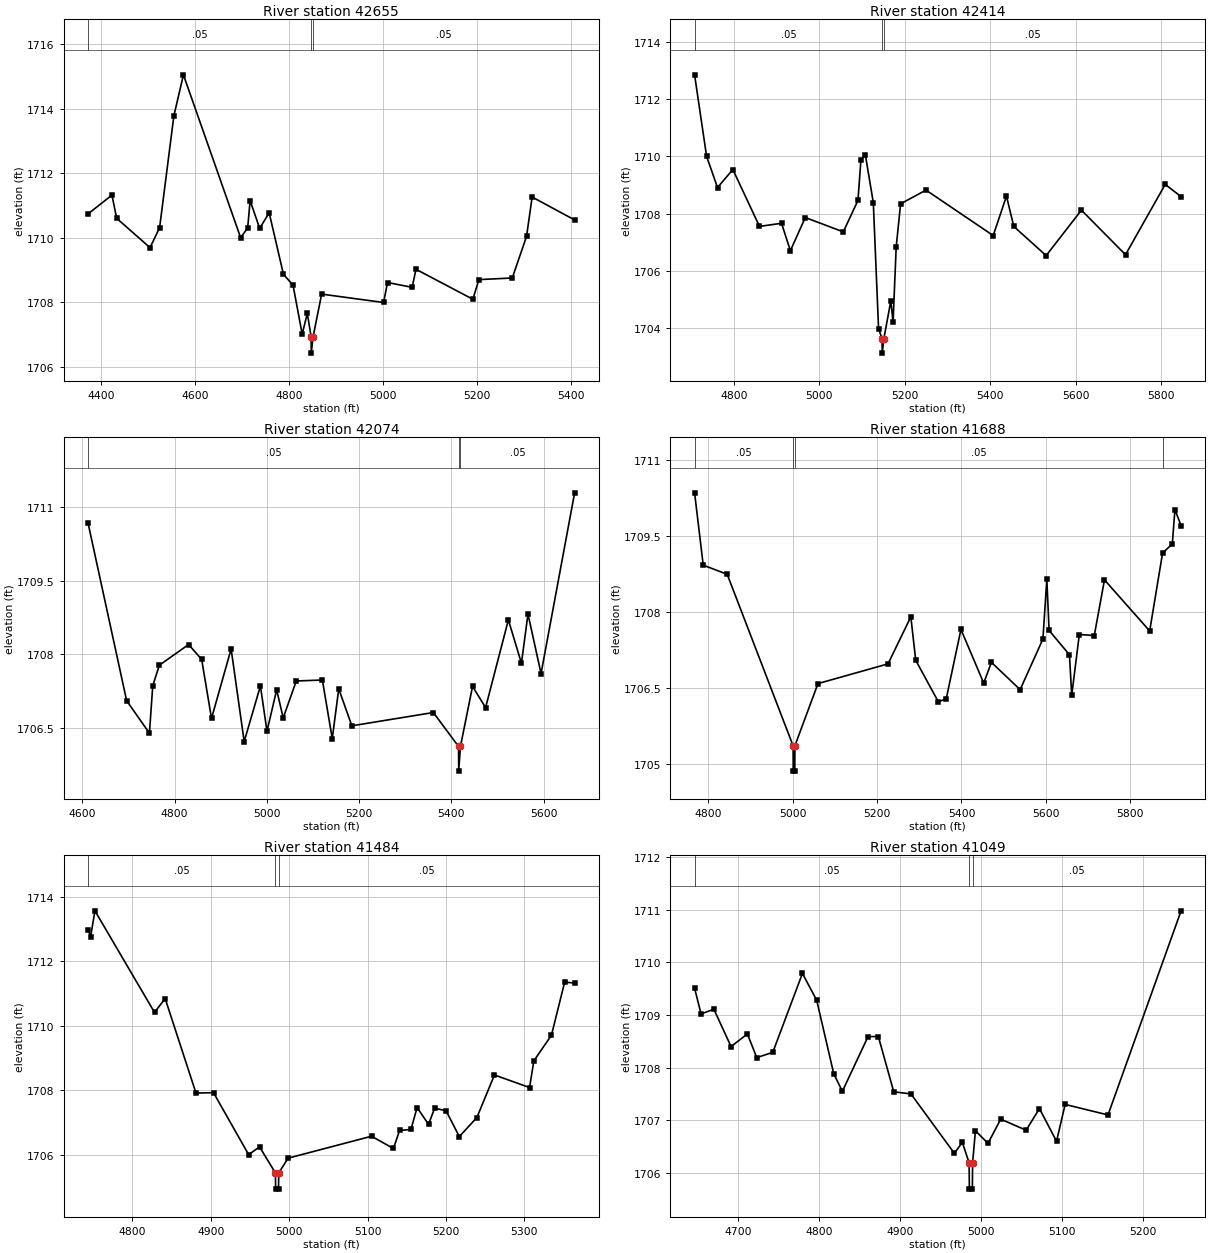
Type RM Length L Ch R = 1,42655,241,241,241
BEGIN DESCRIPTION:
Mapping XS fc222e98
END DESCRIPTION:
XS GIS Cut Line= 2
      1584376.33      6936007.96      1584204.45      6934987.12
#Sta/Elev= 30
  4371.8 1710.74  4422.5 1711.32  4432.6 1710.60  4503.6 1709.69  4523.9 1710.31
  4554.3 1713.78  4574.6 1715.05  4696.3 1710.00  4711.3 1710.30  4716.5 1711.15
  4736.8 1710.29  4757.1 1710.77  4787.5 1708.86  4807.8 1708.53  4827.3 1707.01
  4838.2 1707.65  4846.4 1706.92  4846.6 1706.42  4850.4 1706.92  4868.7 1708.25
  5000.5 1707.99  5008.9 1708.61  5061.3 1708.46  5069.4 1709.02  5190.5 1708.09
  5203.3 1708.70  5274.3 1708.75  5304.7 1710.04  5316.6 1711.26  5407.0 1710.55
#Mann=3,-1,0
  4371.8    0.05       0  4846.4    0.05       0  4850.4    0.05       0
Bank Sta=4846.4,4850.4
Exp/Cntr=0.3,0.1

Type RM Length L Ch R = 1,42414,340,340,340
BEGIN DESCRIPTION:
Mapping XS 2c5812af
END DESCRIPTION:
XS GIS Cut Line= 2
      1584396.95      6935785.20      1584675.35      6934681.98
#Sta/Elev= 30
  4708.4 1712.85  4736.5 1710.00  4762.0 1708.91  4797.9 1709.54  4860.2 1707.55
  4911.8 1707.66  4932.4 1706.70  4967.3 1707.86  5056.2 1707.36  5090.5 1708.46
  5097.4 1709.87  5107.7 1710.06  5126.4 1708.38  5138.7 1703.97  5147.0 1703.62
  5147.2 1703.12  5151.0 1703.62  5167.4 1704.95  5172.6 1704.20  5179.9 1706.83
  5190.2 1708.34  5249.6 1708.82  5406.8 1707.23  5437.8 1708.61  5454.9 1707.55
  5530.6 1706.53  5613.1 1708.12  5716.2 1706.56  5809.1 1709.02  5846.2 1708.59
#Mann=3,-1,0
  4708.4    0.05       0  5147.0    0.05       0  5151.0    0.05       0
Bank Sta=5147,5151
Exp/Cntr=0.3,0.1

Type RM Length L Ch R = 1,42074,386,386,386
BEGIN DESCRIPTION:
Mapping XS f1d99062
END DESCRIPTION:
XS GIS Cut Line= 2
      1584459.60      6935790.67      1585222.77      6935062.83
#Sta/Elev= 30
  4612.5 1710.66  4696.0 1707.06  4745.4 1706.40  4752.6 1707.36  4766.8 1707.78
  4830.3 1708.20  4858.6 1707.90  4880.0 1706.70  4922.5 1708.11  4950.8 1706.23
  4986.0 1707.36  5000.2 1706.44  5021.2 1707.28  5035.4 1706.71  5063.7 1707.46
  5120.3 1707.48  5141.7 1706.29  5155.8 1707.30  5184.2 1706.55  5360.9 1706.82
  5415.5 1706.13  5415.8 1705.63  5419.6 1706.13  5445.8 1707.35  5474.1 1706.92
  5523.5 1708.70  5551.8 1707.82  5566.0 1708.82  5594.3 1707.61  5667.1 1711.28
#Mann=3,-1,0
  4612.5    0.05       0  5415.5    0.05       0  5419.6    0.05       0
Bank Sta=5415.5,5419.6
Exp/Cntr=0.3,0.1

Type RM Length L Ch R = 1,41688,204,204,204
BEGIN DESCRIPTION:
Mapping XS 477d2142
END DESCRIPTION:
XS GIS Cut Line= 3
      1584467.30      6935967.43      1584766.75      6935761.73
      1585498.52      6935464.85
#Sta/Elev= 30
  4767.5 1710.36  4788.0 1708.93  4844.8 1708.75  5001.0 1705.36  5001.3 1704.86
  5005.0 1704.86  5005.2 1705.36  5059.9 1706.59  5226.0 1706.98  5280.0 1707.91
  5291.6 1707.05  5345.2 1706.23  5363.9 1706.29  5398.8 1707.66  5452.7 1706.60
  5471.0 1707.01  5539.0 1706.47  5593.0 1707.47  5602.3 1708.65  5607.7 1707.64
  5655.9 1707.16  5661.3 1706.36  5679.3 1707.56  5714.8 1707.54  5738.9 1708.64
  5846.1 1707.63  5876.6 1709.17  5899.7 1709.35  5905.9 1710.03  5920.5 1709.71
#Mann=4,-1,0
  4767.5    0.05       0  5001.0    0.05       0  5005.2    0.05       0
  5876.6    0.12       0
Bank Sta=5001,5005.2
Exp/Cntr=0.3,0.1

Type RM Length L Ch R = 1,41484,435,435,435
BEGIN DESCRIPTION:
Mapping XS 4b2ffae1
END DESCRIPTION:
XS GIS Cut Line= 2
      1584539.14      6936115.38      1585094.96      6935839.10
#Sta/Elev= 30
  4743.5 1712.97  4746.7 1712.76  4752.2 1713.56  4828.2 1710.41  4841.8 1710.84
  4881.1 1707.91  4903.5 1707.92  4948.3 1706.00  4962.2 1706.24  4982.5 1705.43
  4982.7 1704.93  4986.4 1704.93  4986.7 1705.43  4998.6 1705.89  5105.1 1706.57
  5133.0 1706.19  5140.9 1706.75  5155.4 1706.78  5163.2 1707.46  5177.8 1706.94
  5185.6 1707.44  5200.2 1707.36  5217.1 1706.56  5239.5 1707.15  5261.9 1708.47
  5306.7 1708.08  5312.2 1708.91  5334.6 1709.70  5351.5 1711.35  5364.2 1711.32
#Mann=3,-1,0
  4743.5    0.05       0  4982.5    0.05       0  4986.7    0.05       0
Bank Sta=4982.5,4986.7
Exp/Cntr=0.3,0.1

Type RM Length L Ch R = 1,41049,412,412,412
BEGIN DESCRIPTION:
Mapping XS 7a9fa31d
END DESCRIPTION:
XS GIS Cut Line= 2
      1584937.37      6936480.51      1585132.32      6935912.64
#Sta/Elev= 30
  4646.5 1709.51  4654.5 1709.02  4670.3 1709.11  4691.5 1708.40  4711.7 1708.64
  4723.2 1708.19  4743.0 1708.29  4779.6 1709.79  4797.2 1709.28  4818.3 1707.88
  4828.9 1707.55  4860.6 1708.59  4873.3 1708.59  4892.3 1707.54  4913.5 1707.50
  4967.1 1706.37  4976.9 1706.58  4985.3 1706.19  4985.6 1705.69  4989.3 1705.69
  4989.6 1706.19  4993.1 1706.80  5008.6 1706.56  5024.3 1707.02  5055.6 1706.81
  5072.1 1707.22  5093.2 1706.60  5103.8 1707.30  5156.7 1707.10  5246.9 1710.98
#Mann=3,-1,0
  4646.5    0.05       0  4985.3    0.03       0  4989.6    0.05       0
Bank Sta=4985.3,4989.6
Exp/Cntr=0.3,0.1

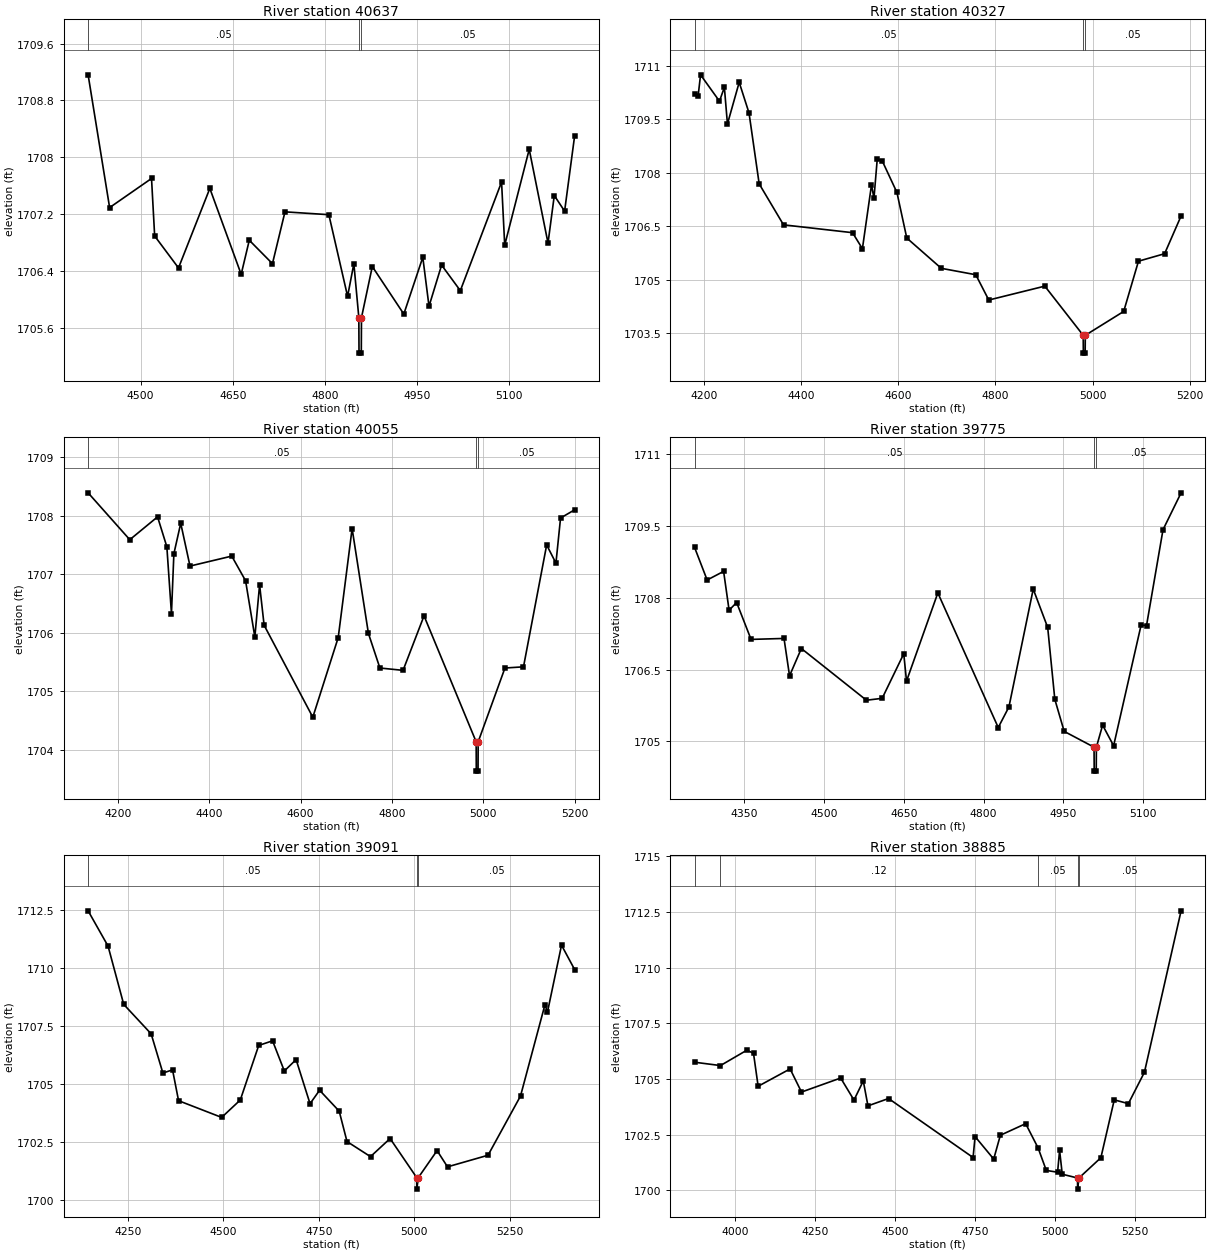
Type RM Length L Ch R = 1,40637,310,310,310
BEGIN DESCRIPTION:
Mapping XS ff8a511a
END DESCRIPTION:
XS GIS Cut Line= 2
      1585259.67      6936632.36      1585412.85      6935855.52
#Sta/Elev= 30
  4414.7 1709.16  4449.7 1707.29  4517.9 1707.70  4523.0 1706.89  4561.8 1706.44
  4612.8 1707.56  4663.8 1706.35  4677.0 1706.83  4714.7 1706.50  4735.1 1707.23
  4806.5 1707.19  4837.0 1706.04  4847.2 1706.50  4855.3 1705.74  4855.6 1705.24
  4859.3 1705.24  4859.6 1705.74  4877.2 1706.46  4928.5 1705.79  4959.4 1706.59
  4969.5 1705.90  4990.0 1706.48  5020.5 1706.12  5087.6 1707.65  5092.7 1706.76
  5132.6 1708.11  5163.2 1706.79  5173.4 1707.46  5190.2 1707.24  5206.5 1708.30
#Mann=3,-1,0
  4414.7    0.05       0  4855.3    0.03       0  4859.6    0.05       0
Bank Sta=4855.3,4859.6
Exp/Cntr=0.3,0.1

Type RM Length L Ch R = 1,40327,272,272,272
BEGIN DESCRIPTION:
Mapping XS 00fc7bc7
END DESCRIPTION:
XS GIS Cut Line= 2
      1585478.50      6936858.47      1585646.02      6935871.58
#Sta/Elev= 30
  4180.9 1710.21  4188.2 1710.16  4193.2 1710.75  4232.1 1710.01  4242.2 1710.40
  4248.5 1709.37  4272.7 1710.54  4292.9 1709.68  4313.8 1707.69  4363.9 1706.54
  4505.9 1706.32  4526.2 1705.87  4544.9 1707.66  4550.0 1707.29  4556.7 1708.38
  4566.8 1708.34  4597.2 1707.45  4617.5 1706.17  4688.5 1705.32  4759.5 1705.14
  4786.2 1704.43  4901.5 1704.82  4980.5 1703.44  4980.8 1702.94  4984.5 1702.94
  4984.8 1703.44  5063.8 1704.11  5094.2 1705.52  5148.0 1705.73  5181.9 1706.79
#Mann=3,-1,0
  4180.9    0.05       0  4980.5    0.05       0  4984.8    0.05       0
Bank Sta=4980.5,4984.8
Exp/Cntr=0.3,0.1

Type RM Length L Ch R = 1,40055,280,280,280
BEGIN DESCRIPTION:
Mapping XS 64a97689
END DESCRIPTION:
XS GIS Cut Line= 2
      1585679.10      6937007.93      1585854.15      6935957.62
#Sta/Elev= 30
  4135.1 1708.39  4226.3 1707.59  4287.1 1707.98  4307.4 1707.47  4317.5 1706.33
  4322.8 1707.35  4337.8 1707.87  4358.1 1707.14  4449.5 1707.31  4479.7 1706.89
  4500.0 1705.93  4510.4 1706.82  4520.3 1706.13  4626.9 1704.56  4682.5 1705.92
  4712.9 1707.78  4748.6 1705.99  4773.7 1705.40  4824.4 1705.36  4870.3 1706.29
  4984.4 1704.14  4984.7 1703.64  4988.5 1703.64  4988.8 1704.14  5047.4 1705.40
  5088.0 1705.42  5138.7 1707.50  5159.0 1707.19  5169.1 1707.96  5199.9 1708.10
#Mann=3,-1,0
  4135.1    0.05       0  4984.4    0.05       0  4988.8    0.05       0
Bank Sta=4984.4,4988.8
Exp/Cntr=0.3,0.1

Type RM Length L Ch R = 1,39775,684,684,684
BEGIN DESCRIPTION:
Mapping XS efec7734
END DESCRIPTION:
XS GIS Cut Line= 2
      1585850.50      6937040.84      1586080.13      6936155.13
#Sta/Elev= 30
  4256.4 1709.05  4280.0 1708.37  4311.0 1708.55  4321.3 1707.74  4335.5 1707.90
  4362.6 1707.13  4424.6 1707.15  4435.0 1706.37  4457.2 1706.94  4579.6 1705.86
  4609.2 1705.90  4649.8 1706.83  4655.0 1706.26  4713.9 1708.10  4827.5 1705.29
  4847.6 1705.72  4893.3 1708.18  4920.5 1707.38  4933.9 1705.88  4951.5 1705.21
  5007.7 1704.88  5008.0 1704.38  5011.8 1704.38  5012.1 1704.88  5023.8 1705.34
  5044.5 1704.91  5096.2 1707.43  5106.4 1707.42  5137.4 1709.42  5171.4 1710.19
#Mann=3,-1,0
  4256.4    0.05       0  5007.7    0.05       0  5012.1    0.05       0
Bank Sta=5007.7,5012.1
Exp/Cntr=0.3,0.1

Type RM Length L Ch R = 1,39091,206,206,206
BEGIN DESCRIPTION:
Mapping XS 31383c63
END DESCRIPTION:
XS GIS Cut Line= 3
      1586361.11      6937328.92      1586579.93      6936366.08
      1586402.40      6936141.45
#Sta/Elev= 30
  4146.3 1712.45  4198.5 1710.93  4239.5 1708.42  4311.3 1707.15  4342.1 1705.46
  4367.3 1705.60  4383.1 1704.27  4495.9 1703.55  4544.7 1704.30  4592.9 1706.65
  4629.2 1706.85  4660.0 1705.55  4690.8 1706.04  4727.3 1704.14  4752.3 1704.72
  4803.6 1703.82  4824.1 1702.51  4885.6 1701.86  4936.9 1702.64  5006.4 1700.96
  5006.8 1700.46  5010.9 1700.96  5059.9 1702.12  5087.2 1701.42  5193.3 1701.92
  5278.3 1704.47  5342.4 1708.41  5348.8 1708.08  5385.7 1710.97  5420.0 1709.92
#Mann=3,-1,0
  4146.3    0.05       0  5006.4    0.03       0  5010.9    0.05       0
Bank Sta=5006.4,5010.9
Exp/Cntr=0.3,0.1

Type RM Length L Ch R = 1,38885,323,323,323
BEGIN DESCRIPTION:
Mapping XS 4c1ee436
END DESCRIPTION:
XS GIS Cut Line= 3
      1587407.82      6937314.32      1586620.05      6936274.91
      1586444.96      6936147.24
#Sta/Elev= 30
  3872.3 1705.75  3953.2 1705.60  4035.7 1706.29  4056.5 1706.15  4071.0 1704.67
  4170.9 1705.45  4206.5 1704.41  4329.0 1705.04  4370.6 1704.05  4399.7 1704.91
  4414.3 1703.79  4478.7 1704.12  4742.9 1701.47  4749.2 1702.41  4807.4 1701.40
  4828.2 1702.47  4907.3 1702.99  4946.2 1701.90  4971.8 1700.89  5007.1 1700.81
  5013.4 1701.79  5021.7 1700.72  5069.4 1700.55  5069.7 1700.05  5073.9 1700.55
  5142.4 1701.46  5184.3 1704.06  5228.4 1703.89  5278.6 1705.30  5393.2 1712.55
#Mann=5,-1,0
  3872.3    0.05       0  3953.2    0.12       0  4946.2    0.05       0
  5069.4    0.03       0  5073.9    0.05       0
Bank Sta=5069.4,5073.9
Exp/Cntr=0.3,0.1

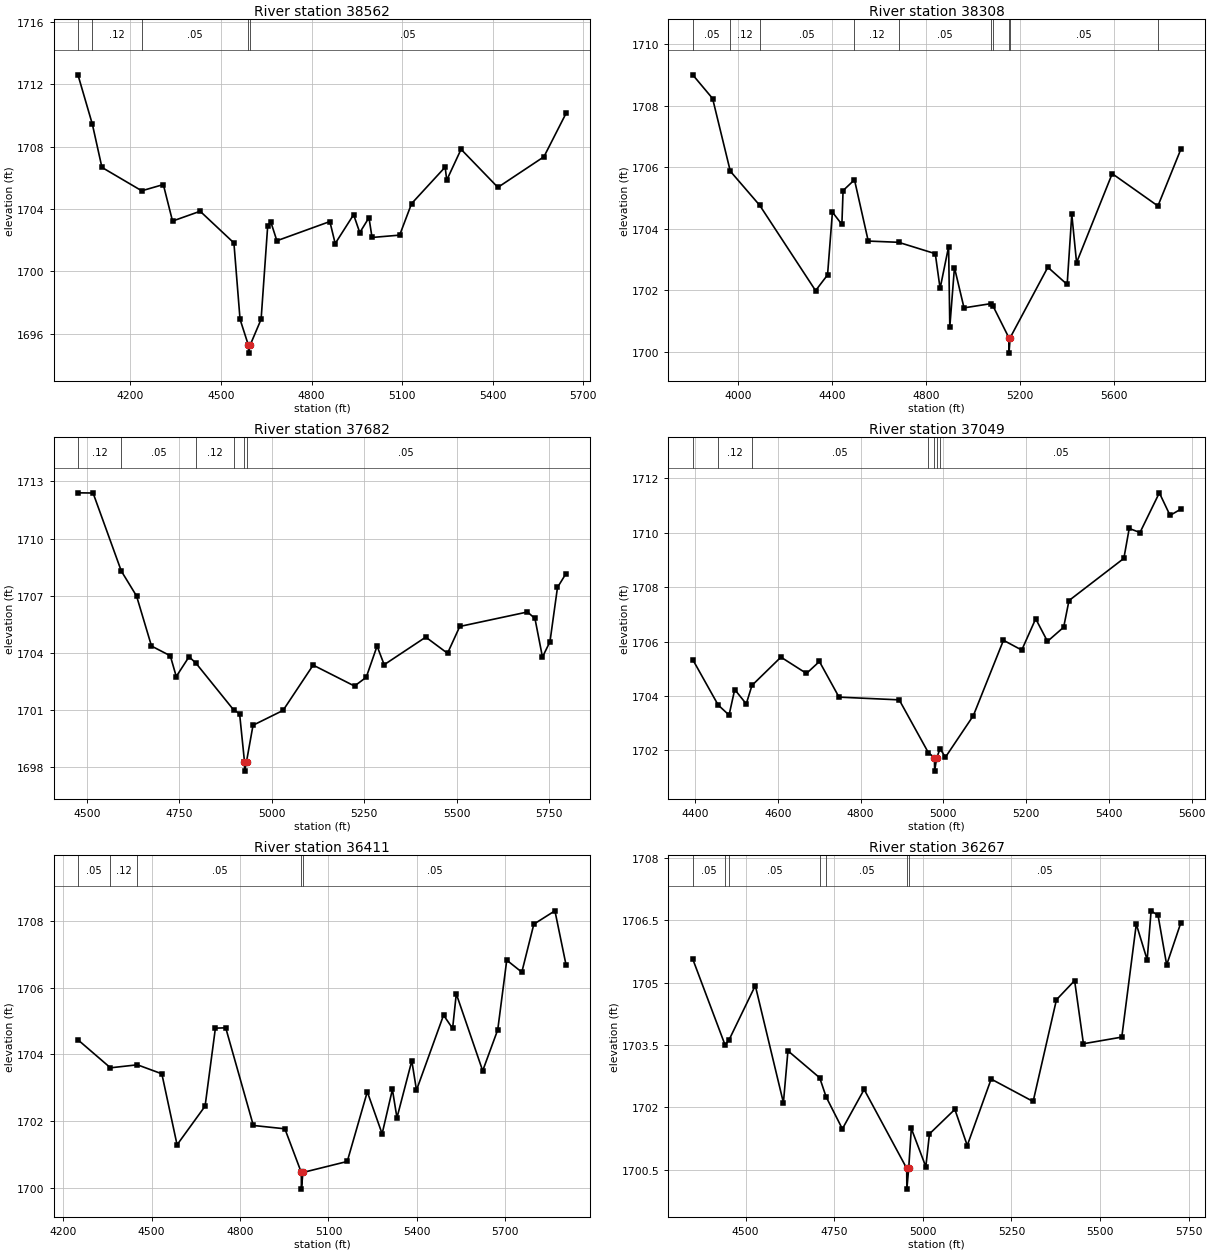
Type RM Length L Ch R = 1,38562,254,254,254
BEGIN DESCRIPTION:
Mapping XS 328e9771
END DESCRIPTION:
XS GIS Cut Line= 2
      1587663.12      6936293.14      1586072.97      6936001.37
#Sta/Elev= 30
  4026.3 1712.60  4074.1 1709.43  4105.7 1706.67  4237.6 1705.17  4309.1 1705.57
  4339.6 1703.23  4431.1 1703.86  4542.9 1701.83  4563.2 1696.94  4591.0 1695.27
  4591.5 1694.77  4596.4 1695.27  4633.0 1696.94  4654.7 1702.89  4664.9 1703.19
  4685.2 1701.97  4860.7 1703.20  4878.4 1701.79  4939.4 1703.64  4959.8 1702.49
  4990.3 1703.45  5000.4 1702.18  5091.9 1702.33  5131.4 1704.35  5242.7 1706.69
  5247.8 1705.85  5295.3 1707.83  5417.3 1705.39  5569.8 1707.35  5643.0 1710.13
#Mann=5,-1,0
  4026.3    0.05       0  4074.1    0.12       0  4237.6    0.05       0
  4591.0    0.03       0  4596.4    0.05       0
Bank Sta=4591,4596.4
Exp/Cntr=0.3,0.1

Type RM Length L Ch R = 1,38308,626,626,626
BEGIN DESCRIPTION:
Mapping XS f3a7355d
END DESCRIPTION:
XS GIS Cut Line= 2
      1587757.99      6936191.03      1585719.65      6935775.34
#Sta/Elev= 30
  3805.4 1709.00  3890.1 1708.23  3965.5 1705.87  4091.0 1704.76  4329.0 1701.99
  4380.0 1702.50  4400.8 1704.54  4441.1 1704.14  4446.2 1705.24  4494.8 1705.59
  4553.5 1703.60  4682.7 1703.56  4839.2 1703.19  4859.7 1702.06  4896.0 1703.42
  4901.1 1700.81  4920.9 1702.74  4961.7 1701.43  5078.2 1701.57  5084.6 1701.50
  5152.9 1700.46  5153.4 1699.96  5158.3 1700.46  5318.9 1702.75  5401.3 1702.19
  5421.0 1704.47  5441.4 1702.90  5593.3 1705.79  5788.1 1704.74  5885.7 1706.58
#Mann=10,-1,0
  3805.4    0.05       0  3965.5    0.12       0  4091.0    0.05       0
  4494.8    0.12       0  4682.7    0.05       0  5078.2    0.12       0
  5084.6    0.05       0  5152.9    0.03       0  5158.3    0.05       0
  5788.1    0.12       0
Bank Sta=5152.9,5158.3
Exp/Cntr=0.3,0.1

Type RM Length L Ch R = 1,37682,633,633,633
BEGIN DESCRIPTION:
Mapping XS 0475cbcb
END DESCRIPTION:
XS GIS Cut Line= 2
      1587130.69      6935355.83      1585832.31      6935589.24
#Sta/Elev= 30
  4476.1 1712.40  4517.0 1712.39  4593.3 1708.29  4634.5 1706.98  4674.9 1704.35
  4725.7 1703.84  4741.8 1702.75  4776.5 1703.79  4795.5 1703.44  4896.7 1701.00
  4913.0 1700.80  4926.2 1698.28  4926.6 1697.78  4931.7 1698.28  4949.3 1700.19
  5030.5 1700.97  5111.8 1703.35  5223.6 1702.25  5255.3 1702.71  5284.6 1704.35
  5303.8 1703.37  5416.2 1704.82  5475.0 1703.97  5508.1 1705.38  5691.0 1706.14
  5711.3 1705.80  5731.6 1703.77  5751.9 1704.58  5772.2 1707.43  5795.3 1708.16
#Mann=6,-1,0
  4476.1    0.12       0  4593.3    0.05       0  4795.5    0.12       0
  4896.7    0.05       0  4926.2    0.05       0  4931.7    0.05       0
Bank Sta=4926.2,4931.7
Exp/Cntr=0.3,0.1

Type RM Length L Ch R = 1,37049,638,638,638
BEGIN DESCRIPTION:
Mapping XS 3d98ff44
END DESCRIPTION:
XS GIS Cut Line= 2
      1586689.39      6934965.58      1585555.12      6935290.18
#Sta/Elev= 30
  4394.1 1705.34  4455.6 1703.67  4481.9 1703.30  4495.6 1704.24  4523.5 1703.71
  4537.2 1704.39  4607.3 1705.43  4669.1 1704.83  4700.3 1705.27  4747.7 1703.96
  4893.2 1703.86  4964.0 1701.91  4978.4 1701.74  4978.8 1701.24  4983.9 1701.74
  4992.0 1702.06  5004.9 1701.75  5072.4 1703.28  5145.2 1706.05  5189.4 1705.69
  5223.1 1706.84  5251.6 1706.01  5290.7 1706.53  5303.6 1707.51  5436.2 1709.06
  5449.2 1710.16  5475.2 1710.01  5522.0 1711.47  5547.9 1710.64  5573.9 1710.87
#Mann=7,-1,0
  4394.1    0.05       0  4455.6    0.12       0  4537.2    0.05       0
  4964.0    0.12       0  4978.4    0.05       0  4983.9    0.12       0
  4992.0    0.05       0
Bank Sta=4978.4,4983.9
Exp/Cntr=0.3,0.1

Type RM Length L Ch R = 1,36411,144,144,144
BEGIN DESCRIPTION:
Deadman 07 48.0
END DESCRIPTION:
XS GIS Cut Line= 3
      1586830.03      6934863.01      1586101.67      6934669.29
      1585218.08      6934487.37
#Sta/Elev= 30
  4250.2 1704.44  4360.5 1703.60  4451.9 1703.69  4534.8 1703.42  4586.5 1701.29
  4681.5 1702.45  4716.5 1704.79  4751.5 1704.80  4845.2 1701.87  4952.2 1701.77
  5007.9 1700.46  5008.3 1699.96  5013.4 1700.46  5163.8 1700.79  5231.8 1702.88
  5282.1 1701.62  5317.0 1702.95  5332.4 1702.10  5382.8 1703.81  5398.7 1702.93
  5490.5 1705.18  5521.2 1704.78  5533.7 1705.82  5623.3 1703.51  5674.3 1704.74
  5704.9 1706.83  5756.0 1706.47  5796.8 1707.91  5868.3 1708.31  5906.0 1706.69
#Mann=5,-1,0
  4250.2    0.05       0  4360.5    0.12       0  4451.9    0.05       0
  5007.9    0.05       0  5013.4    0.05       0
Bank Sta=5007.9,5013.4
Exp/Cntr=0.3,0.1

Type RM Length L Ch R = 1,36267,510,510,510
BEGIN DESCRIPTION:
Mapping XS 06a5b671
END DESCRIPTION:
XS GIS Cut Line= 2
      1586697.39      6934678.14      1585352.33      6934384.20
#Sta/Elev= 30
  4351.1 1705.57  4442.3 1703.50  4453.4 1703.62  4527.6 1704.93  4606.9 1702.11
  4619.7 1703.36  4709.3 1702.71  4727.4 1702.25  4773.2 1701.48  4834.6 1702.43
  4954.7 1700.53  4955.1 1700.03  4960.3 1700.53  4967.7 1701.49  5008.6 1700.57
  5018.9 1701.36  5090.5 1701.95  5125.5 1701.08  5192.9 1702.68  5311.3 1702.14
  5377.1 1704.59  5428.3 1705.05  5453.2 1703.53  5561.4 1703.69  5602.3 1706.41
  5633.0 1705.55  5644.1 1706.73  5663.7 1706.62  5688.0 1705.43  5727.9 1706.44
#Mann=7,-1,0
  4351.1    0.05       0  4442.3    0.12       0  4453.4    0.05       0
  4709.3    0.12       0  4727.4    0.05       0  4954.7    0.05       0
  4960.3    0.05       0
Bank Sta=4954.7,4960.3
Exp/Cntr=0.3,0.1

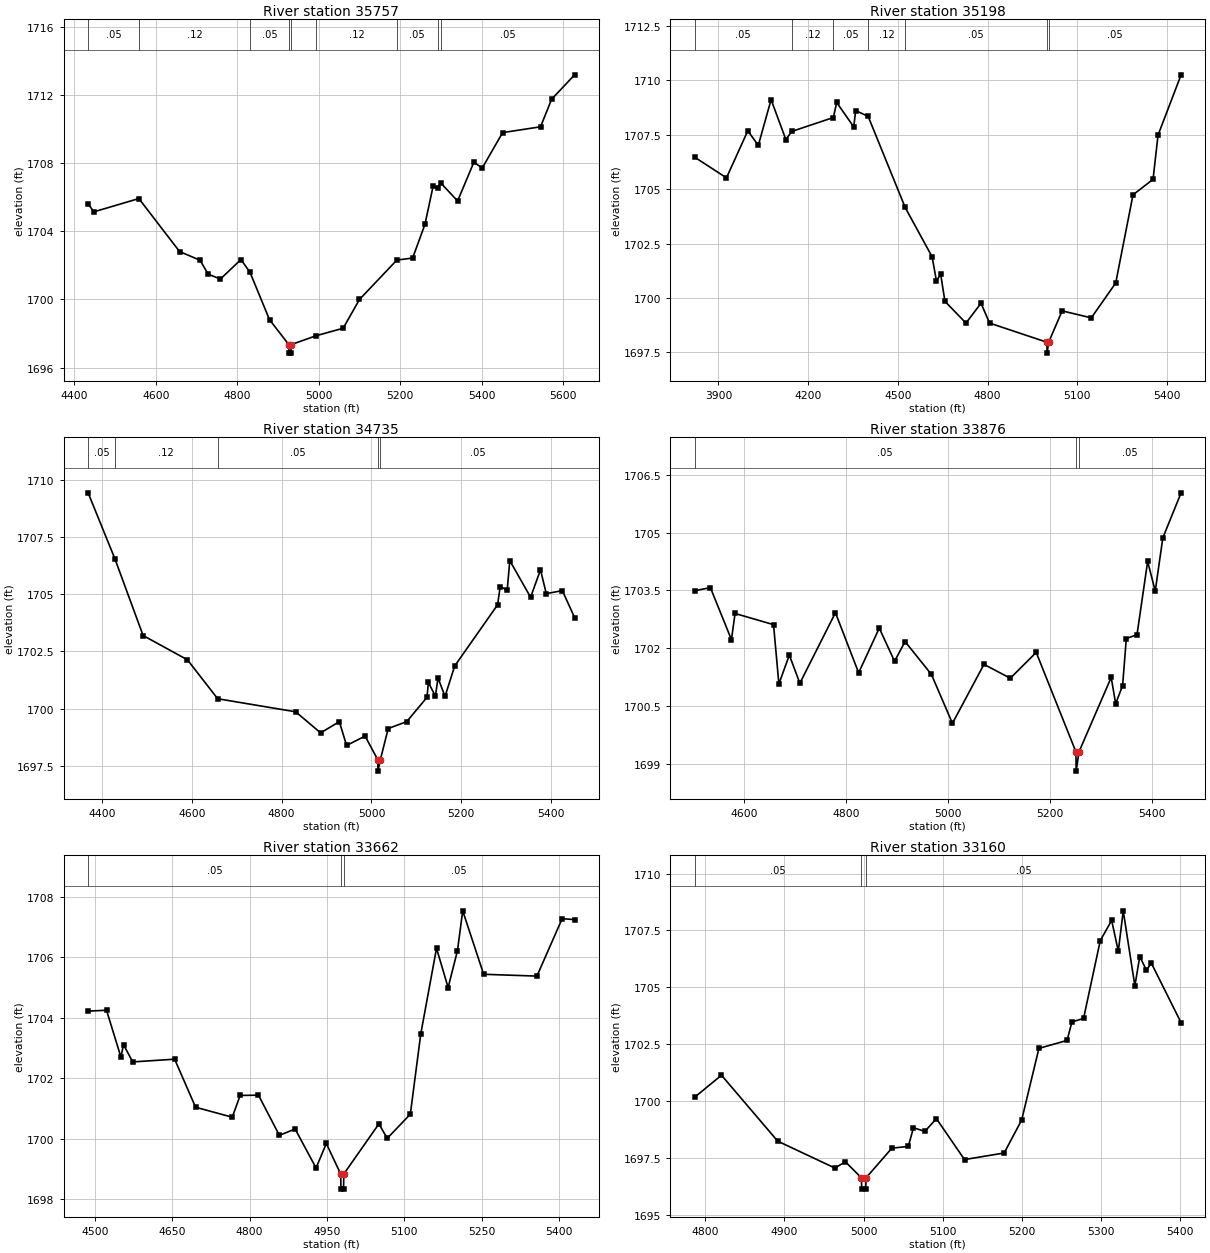
Type RM Length L Ch R = 1,35757,559,559,559
BEGIN DESCRIPTION:
Mapping XS 3a71ffa4
END DESCRIPTION:
XS GIS Cut Line= 3
      1586586.86      6934224.33      1586415.17      6934113.79
      1585428.80      6934036.29
#Sta/Elev= 30
  4434.1 1705.61  4448.2 1705.14  4558.6 1705.92  4658.5 1702.81  4708.7 1702.30
  4728.7 1701.48  4758.8 1701.20  4809.0 1702.34  4831.1 1701.60  4879.2 1698.81
  4926.5 1697.35  4927.0 1696.85  4931.8 1696.85  4932.2 1697.35  4993.3 1697.87
  5059.8 1698.31  5099.9 1700.00  5191.5 1702.31  5230.3 1702.43  5260.4 1704.40
  5280.4 1706.63  5291.4 1706.55  5299.0 1706.84  5340.6 1705.78  5380.7 1708.06
  5400.8 1707.70  5451.0 1709.79  5544.1 1710.13  5571.3 1711.75  5627.7 1713.18
#Mann=9,-1,0
  4434.1    0.05       0  4558.6    0.12       0  4831.1    0.05       0
  4926.5    0.07       0  4932.2    0.05       0  4993.3    0.12       0
  5191.5    0.05       0  5291.4    0.12       0  5299.0    0.05       0
Bank Sta=4926.5,4932.2
Exp/Cntr=0.3,0.1

Type RM Length L Ch R = 1,35198,463,463,463
BEGIN DESCRIPTION:
Deadman 07 47.0
END DESCRIPTION:
XS GIS Cut Line= 3
      1586852.54      6934361.12      1585955.00      6933588.00
      1585559.60      6933389.14
#Sta/Elev= 30
  3820.1 1706.47  3926.8 1705.52  3998.1 1707.68  4033.2 1707.01  4076.0 1709.11
  4125.3 1707.28  4145.1 1707.65  4284.3 1708.29  4295.4 1708.98  4352.4 1707.86
  4359.0 1708.61  4400.7 1708.34  4524.4 1704.16  4614.7 1701.89  4628.9 1700.79
  4643.2 1701.09  4657.4 1699.85  4727.7 1698.85  4778.1 1699.76  4806.7 1698.85
  4998.5 1697.97  4999.0 1697.47  5004.4 1697.97  5049.5 1699.41  5147.0 1699.09
  5228.6 1700.69  5286.5 1704.74  5353.5 1705.45  5370.2 1707.48  5447.3 1710.25
#Mann=7,-1,0
  3820.1    0.05       0  4145.1    0.12       0  4284.3    0.05       0
  4400.7    0.12       0  4524.4    0.05       0  4998.5    0.05       0
  5004.4    0.05       0
Bank Sta=4998.5,5004.4
Exp/Cntr=0.3,0.1

Type RM Length L Ch R = 1,34735,859,859,859
BEGIN DESCRIPTION:
Mapping XS 24f9ce81
END DESCRIPTION:
XS GIS Cut Line= 3
      1586452.80      6933906.87      1586273.45      6933174.15
      1585990.74      6933006.54
#Sta/Elev= 30
  4369.2 1709.42  4429.2 1706.52  4491.6 1703.19  4590.3 1702.13  4657.6 1700.43
  4831.3 1699.86  4886.8 1698.94  4928.4 1699.43  4944.6 1698.39  4985.7 1698.80
  5013.9 1697.77  5014.4 1697.27  5019.8 1697.77  5037.2 1699.13  5078.4 1699.43
  5123.5 1700.49  5126.7 1701.14  5142.3 1700.54  5148.1 1701.34  5163.7 1700.53
  5185.2 1701.86  5280.7 1704.53  5286.5 1705.33  5302.1 1705.17  5307.9 1706.46
  5354.2 1704.86  5376.2 1706.06  5389.1 1705.02  5424.9 1705.15  5452.2 1703.97
#Mann=5,-1,0
  4369.2    0.05       0  4429.2    0.12       0  4657.6    0.05       0
  5013.9    0.03       0  5019.8    0.05       0
Bank Sta=5013.9,5019.8
Exp/Cntr=0.3,0.1

Type RM Length L Ch R = 1,33876,214,214,214
BEGIN DESCRIPTION:
Mapping XS 6a7003a7
END DESCRIPTION:
XS GIS Cut Line= 3
      1587445.10      6933603.53      1586687.94      6933406.01
      1586589.72      6933263.35
#Sta/Elev= 30
  4502.4 1703.49  4533.5 1703.57  4574.8 1702.22  4581.9 1702.90  4657.5 1702.61
  4668.0 1701.07  4688.5 1701.82  4709.2 1701.09  4779.1 1702.92  4824.7 1701.36
  4865.2 1702.52  4895.2 1701.66  4915.9 1702.17  4967.6 1701.32  5008.9 1700.05
  5070.9 1701.58  5122.6 1701.22  5173.5 1701.89  5251.5 1699.31  5252.0 1698.81
  5257.5 1699.31  5320.8 1701.24  5329.6 1700.56  5343.2 1701.03  5350.5 1702.25
  5371.5 1702.35  5392.4 1704.25  5407.3 1703.48  5422.2 1704.86  5458.1 1706.03
#Mann=3,-1,0
  4502.4    0.05       0  5251.5    0.05       0  5257.5    0.05       0
Bank Sta=5251.5,5257.5
Exp/Cntr=0.3,0.1

Type RM Length L Ch R = 1,33662,502,502,502
BEGIN DESCRIPTION:
Mapping XS d36ae7a7
END DESCRIPTION:
XS GIS Cut Line= 2
      1587460.18      6933384.57      1586531.31      6933219.63
#Sta/Elev= 30
  4486.7 1704.22  4522.4 1704.25  4550.3 1702.70  4555.4 1703.11  4573.2 1702.54
  4654.5 1702.63  4695.1 1701.04  4766.2 1700.71  4781.5 1701.43  4817.0 1701.44
  4857.6 1700.11  4888.1 1700.32  4928.7 1699.03  4948.6 1699.84  4976.5 1698.83
  4977.0 1698.33  4982.0 1698.33  4982.5 1698.83  5050.6 1700.49  5066.7 1700.01
  5111.5 1700.81  5131.8 1703.47  5162.3 1706.30  5184.8 1705.00  5202.9 1706.22
  5213.1 1707.54  5253.7 1705.44  5357.0 1705.38  5405.9 1707.28  5430.1 1707.25
#Mann=3,-1,0
  4486.7    0.05       0  4976.5    0.03       0  4982.5    0.05       0
Bank Sta=4976.5,4982.5
Exp/Cntr=0.3,0.1

Type RM Length L Ch R = 1,33160,432,432,432
BEGIN DESCRIPTION:
Mapping XS aeba6826
END DESCRIPTION:
XS GIS Cut Line= 2
      1586917.61      6932802.99      1586422.82      6933167.57
#Sta/Elev= 30
  4786.5 1700.16  4820.5 1701.13  4891.5 1698.23  4963.6 1697.05  4977.1 1697.32
  4997.2 1696.62  4997.7 1696.12  5002.7 1696.12  5003.2 1696.62  5035.7 1697.92
  5056.5 1698.00  5063.0 1698.82  5077.4 1698.66  5092.0 1699.22  5127.5 1697.42
  5177.6 1697.71  5199.7 1699.16  5221.5 1702.31  5257.0 1702.66  5263.2 1703.47
  5277.9 1703.63  5299.0 1707.05  5313.4 1707.94  5321.8 1706.58  5328.0 1708.36
  5342.7 1705.06  5348.9 1706.35  5357.3 1705.75  5363.5 1706.06  5401.1 1703.44
#Mann=3,-1,0
  4786.5    0.05       0  4997.2    0.03       0  5003.2    0.05       0
Bank Sta=4997.2,5003.2
Exp/Cntr=0.3,0.1

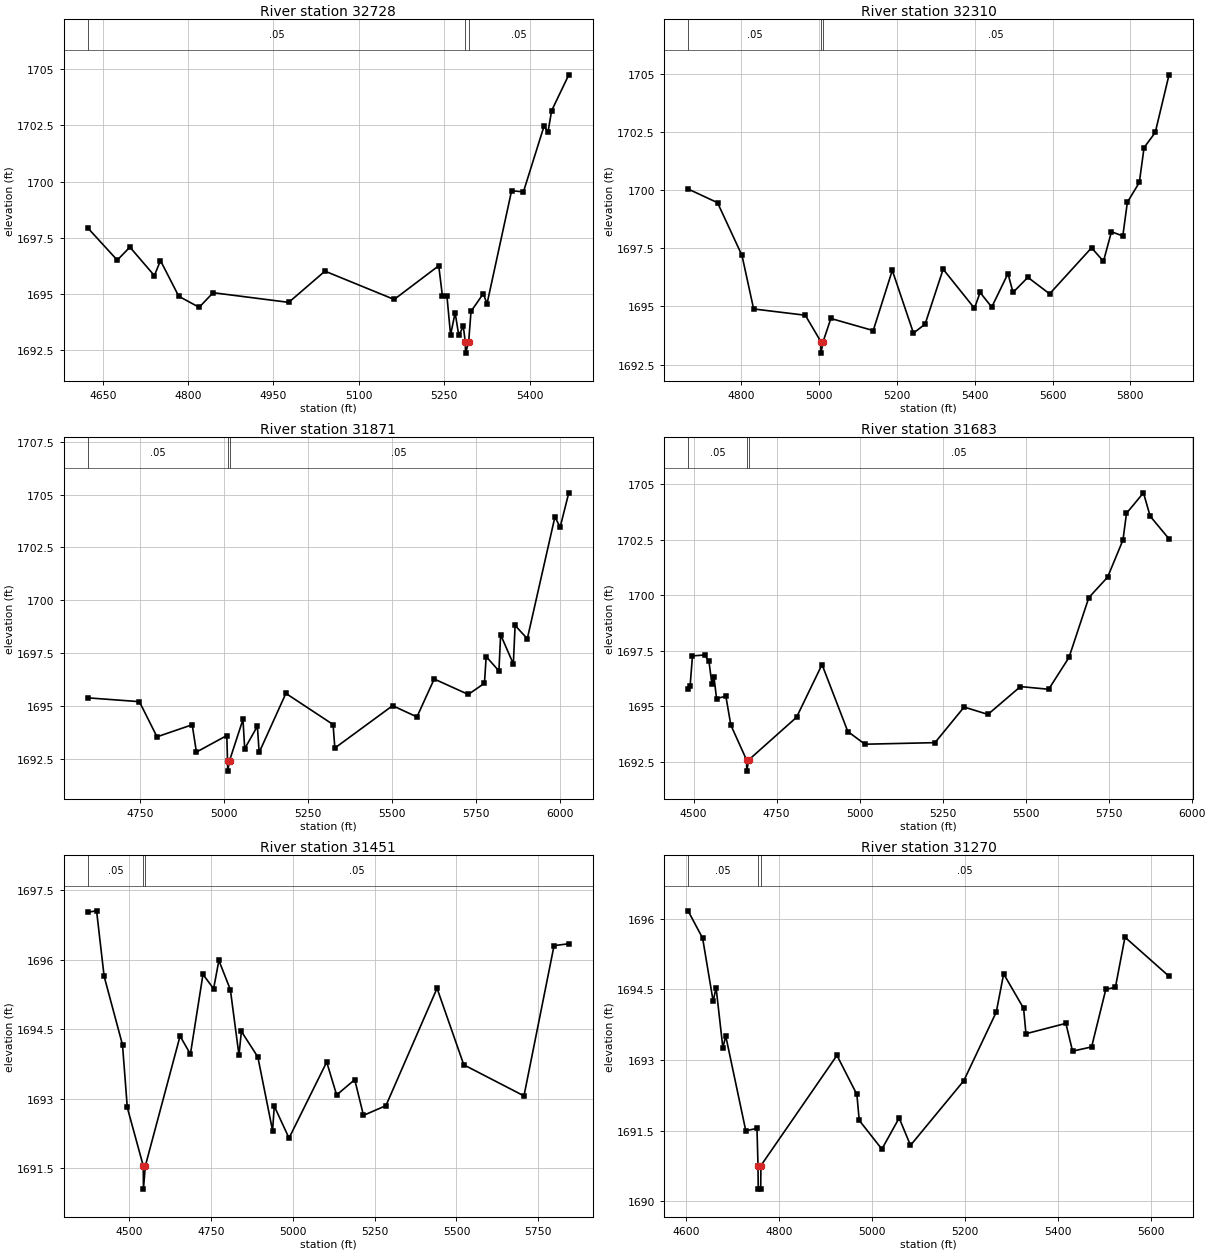
Type RM Length L Ch R = 1,32728,418,418,418
BEGIN DESCRIPTION:
Mapping XS 27f7dca7
END DESCRIPTION:
XS GIS Cut Line= 3
      1586843.89      6932542.54      1586487.96      6932681.44
      1586197.18      6933041.65
#Sta/Elev= 30
  4623.9 1697.93  4675.6 1696.50  4697.8 1697.08  4740.8 1695.81  4751.5 1696.48
  4783.7 1694.89  4819.5 1694.40  4844.0 1695.05  4976.9 1694.62  5040.5 1696.01
  5162.1 1694.75  5240.4 1696.25  5246.8 1694.92  5254.8 1694.90  5261.2 1693.17
  5269.2 1694.16  5275.6 1693.15  5283.6 1693.55  5287.0 1692.86  5287.5 1692.36
  5293.0 1692.86  5297.1 1694.22  5318.8 1695.01  5325.2 1694.55  5368.4 1699.59
  5389.2 1699.54  5425.6 1702.48  5432.3 1702.19  5438.7 1703.15  5468.9 1704.75
#Mann=3,-1,0
  4623.9    0.05       0  5287.0    0.05       0  5293.0    0.05       0
Bank Sta=5287,5293
Exp/Cntr=0.3,0.1

Type RM Length L Ch R = 1,32310,439,439,439
BEGIN DESCRIPTION:
Mapping XS 0678492d
END DESCRIPTION:
XS GIS Cut Line= 3
      1586865.55      6932221.38      1586218.86      6932473.11
      1586106.00      6933002.66
#Sta/Elev= 30
  4663.9 1700.05  4739.6 1699.46  4802.4 1697.19  4832.3 1694.89  4965.0 1694.62
  5004.8 1693.49  5005.3 1692.99  5010.9 1693.49  5030.7 1694.48  5139.5 1693.96
  5188.5 1696.55  5242.9 1693.85  5272.8 1694.24  5319.1 1696.60  5399.5 1694.92
  5414.0 1695.60  5443.9 1694.97  5485.6 1696.41  5498.6 1695.60  5536.7 1696.25
  5592.6 1695.54  5700.3 1697.52  5730.9 1696.94  5751.4 1698.21  5780.6 1698.03
  5792.3 1699.48  5823.0 1700.33  5835.2 1701.83  5863.9 1702.48  5899.3 1704.96
#Mann=3,-1,0
  4663.9    0.05       0  5004.8    0.03       0  5010.9    0.05       0
Bank Sta=5004.8,5010.9
Exp/Cntr=0.3,0.1

Type RM Length L Ch R = 1,31871,188,188,188
BEGIN DESCRIPTION:
Mapping XS f4117f0d
END DESCRIPTION:
XS GIS Cut Line= 3
      1586388.13      6931600.70      1586314.35      6931991.34
      1586084.32      6932998.25
#Sta/Elev= 30
  4595.0 1695.40  4748.3 1695.22  4800.7 1693.56  4905.4 1694.13  4917.9 1692.84
  5008.3 1693.62  5010.4 1692.44  5010.9 1691.94  5016.5 1692.44  5056.4 1694.38
  5061.5 1693.00  5099.3 1694.06  5104.5 1692.82  5184.0 1695.61  5324.4 1694.14
  5329.6 1693.03  5501.4 1695.03  5573.8 1694.50  5625.1 1696.29  5726.5 1695.56
  5774.6 1696.09  5779.7 1697.35  5817.6 1696.67  5822.7 1698.38  5860.5 1697.00
  5865.7 1698.82  5902.0 1698.19  5984.1 1703.94  5999.7 1703.46  6025.4 1705.08
#Mann=3,-1,0
  4595.0    0.05       0  5010.4    0.03       0  5016.5    0.05       0
Bank Sta=5010.4,5016.5
Exp/Cntr=0.3,0.1

Type RM Length L Ch R = 1,31683,232,232,232
BEGIN DESCRIPTION:
Mapping XS 9daa80c3
END DESCRIPTION:
XS GIS Cut Line= 3
      1586336.02      6931570.35      1586201.50      6931661.47
      1585954.26      6932923.71
#Sta/Elev= 30
  4483.1 1695.76  4489.1 1695.90  4496.4 1697.27  4532.6 1697.31  4546.0 1697.03
  4555.0 1695.99  4561.0 1696.34  4568.9 1695.35  4596.9 1695.46  4611.9 1694.16
  4659.4 1692.59  4659.9 1692.09  4665.5 1692.59  4809.8 1694.51  4886.6 1696.88
  4964.3 1693.87  5015.8 1693.30  5226.8 1693.37  5314.6 1694.97  5386.4 1694.64
  5484.2 1695.89  5569.3 1695.77  5630.5 1697.20  5690.2 1699.89  5746.8 1700.81
  5793.1 1702.48  5803.7 1703.68  5854.8 1704.60  5875.0 1703.55  5931.8 1702.53
#Mann=3,-1,0
  4483.1    0.05       0  4659.4    0.05       0  4665.5    0.05       0
Bank Sta=4659.4,4665.5
Exp/Cntr=0.3,0.1

Type RM Length L Ch R = 1,31451,181,181,181
BEGIN DESCRIPTION:
Mapping XS 9917348e
END DESCRIPTION:
XS GIS Cut Line= 4
      1586306.29      6931570.62      1586183.82      6931662.47
      1586116.74      6931964.33      1585130.96      6931760.17
#Sta/Elev= 30
  4374.1 1697.02  4400.8 1697.05  4423.8 1695.64  4480.0 1694.16  4494.6 1692.81
  4543.4 1691.55  4543.9 1691.05  4549.7 1691.55  4655.8 1694.35  4687.4 1693.96
  4725.8 1695.68  4758.2 1695.37  4774.4 1695.98  4809.4 1695.35  4835.7 1693.94
  4843.1 1694.45  4893.3 1693.90  4938.4 1692.31  4943.5 1692.84  4988.6 1692.15
  5103.7 1693.79  5134.0 1693.08  5189.3 1693.41  5216.0 1692.64  5284.6 1692.85
  5440.7 1695.38  5522.4 1693.73  5706.2 1693.06  5798.1 1696.30  5843.1 1696.34
#Mann=3,-1,0
  4374.1    0.05       0  4543.4    0.05       0  4549.7    0.05       0
Bank Sta=4543.4,4549.7
Exp/Cntr=0.3,0.1

Type RM Length L Ch R = 1,31270,254,254,254
BEGIN DESCRIPTION:
Mapping XS 7d109312
END DESCRIPTION:
XS GIS Cut Line= 4
      1586278.49      6931576.81      1586179.51      6931652.35
      1586122.22      6931792.98      1585382.60      6931623.70
#Sta/Elev= 30
  4603.4 1696.17  4634.7 1695.59  4657.4 1694.25  4663.7 1694.54  4678.3 1693.26
  4684.5 1693.51  4727.6 1691.50  4751.7 1691.55  4753.9 1690.76  4754.4 1690.26
  4759.7 1690.26  4760.2 1690.76  4923.8 1693.10  4966.7 1692.27  4971.8 1691.72
  5020.5 1691.11  5057.7 1691.77  5082.1 1691.19  5196.7 1692.56  5266.7 1694.02
  5282.6 1694.83  5325.5 1694.10  5330.6 1693.56  5416.5 1693.78  5430.9 1693.19
  5471.9 1693.28  5502.4 1694.50  5523.2 1694.55  5543.7 1695.61  5638.5 1694.78
#Mann=3,-1,0
  4603.4    0.05       0  4753.9    0.05       0  4760.2    0.05       0
Bank Sta=4753.9,4760.2
Exp/Cntr=0.3,0.1