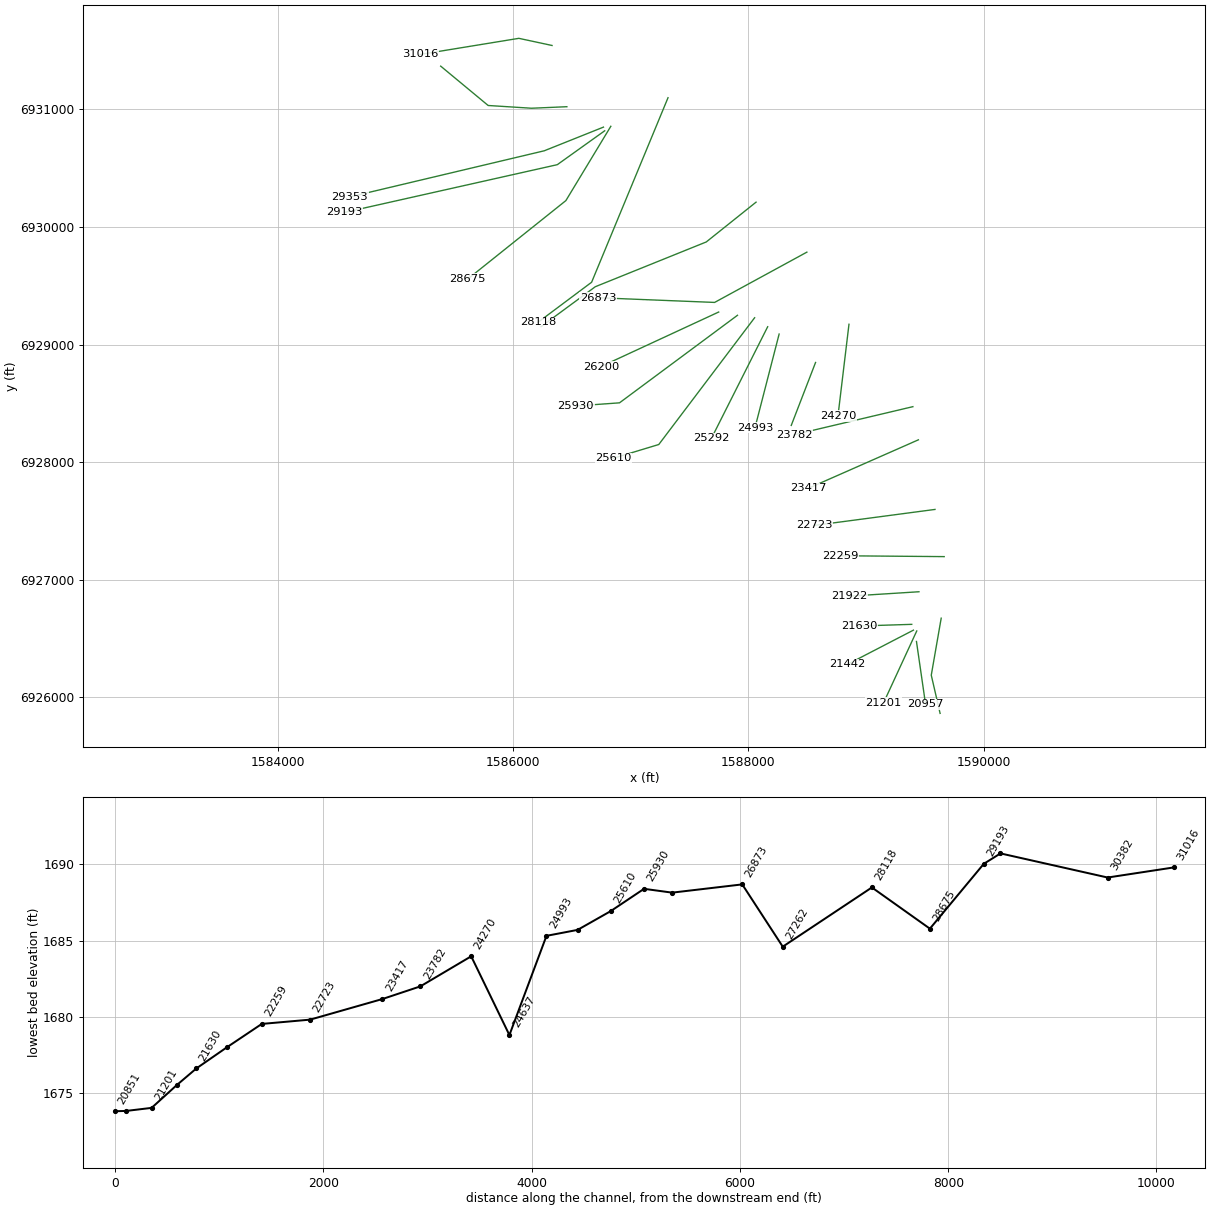
HEC-RAS study Deadman 07.prj: Deadman 07 Base Level Engineering

--- Deadman 07.g01 (geometry) --- (continued)

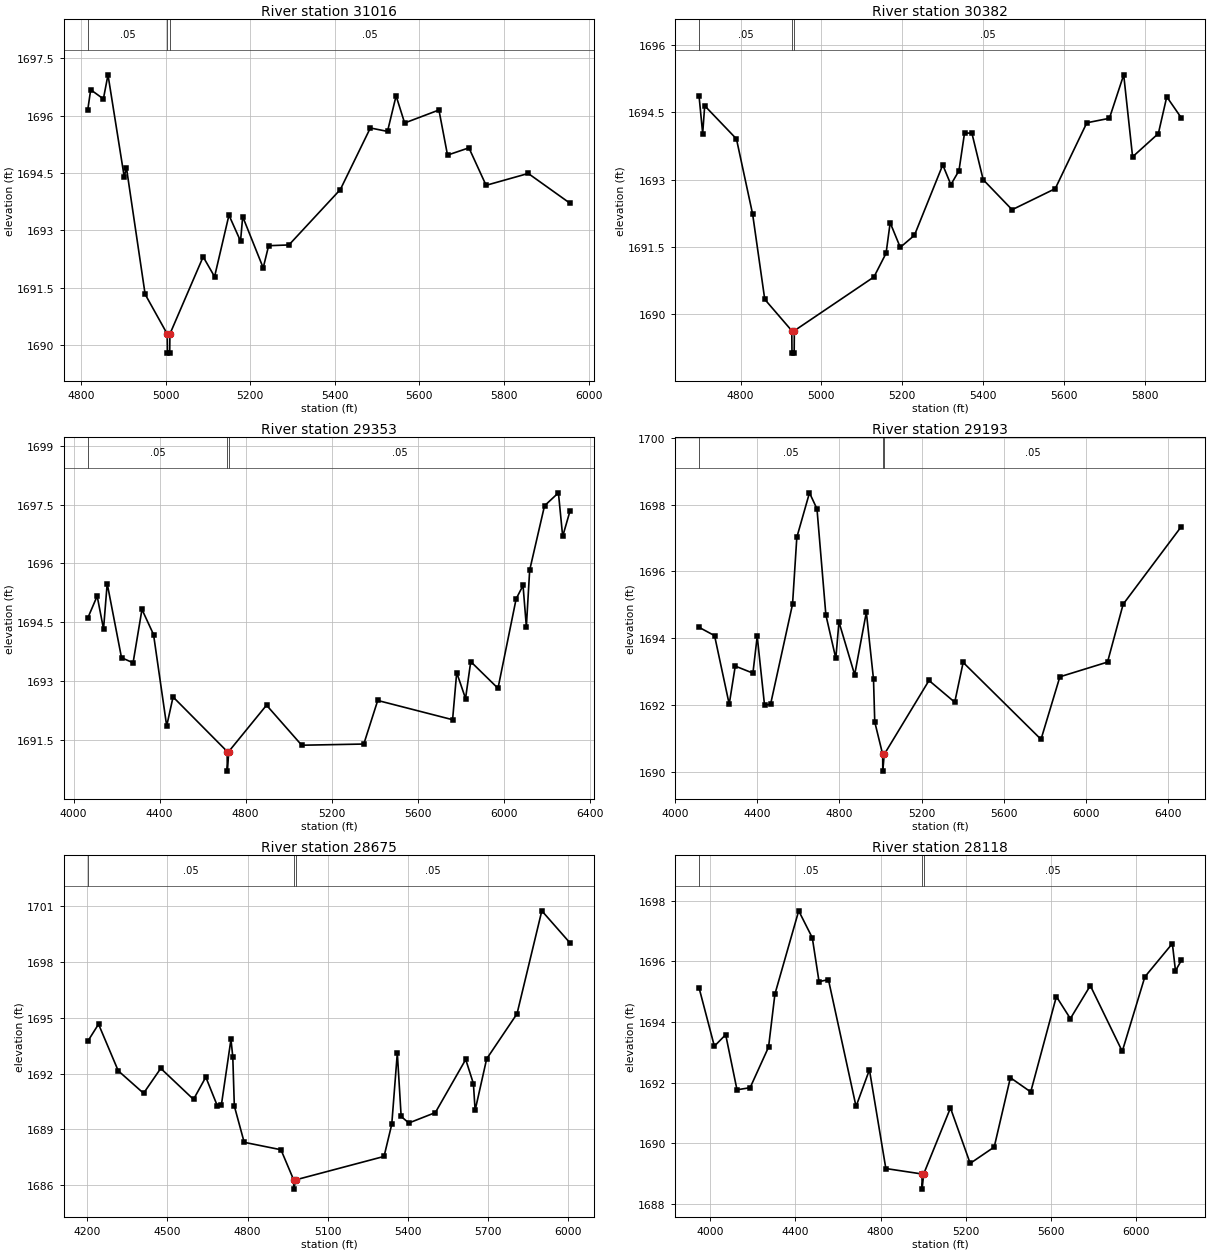
Type RM Length L Ch R = 1,31016,634,634,634
BEGIN DESCRIPTION:
Mapping XS 6cad25dc
END DESCRIPTION:
XS GIS Cut Line= 3
      1586331.72      6931544.28      1586049.59      6931605.05
      1585209.06      6931467.60
#Sta/Elev= 30
  4816.0 1696.16  4822.9 1696.68  4852.9 1696.44  4863.8 1697.07  4902.2 1694.40
  4907.4 1694.64  4951.6 1691.33  5003.9 1690.29  5004.4 1689.79  5009.7 1689.79
  5010.2 1690.29  5088.8 1692.31  5115.8 1691.79  5149.8 1693.40  5177.2 1692.72
  5182.3 1693.36  5230.8 1692.02  5243.6 1692.60  5291.6 1692.62  5413.2 1694.07
  5484.1 1695.68  5524.7 1695.59  5545.0 1696.52  5565.2 1695.81  5646.3 1696.15
  5666.6 1694.97  5717.2 1695.16  5757.8 1694.18  5857.5 1694.49  5956.3 1693.71
#Mann=3,-1,0
  4816.0    0.05       0  5003.9    0.05       0  5010.2    0.05       0
Bank Sta=5003.9,5010.2
Exp/Cntr=0.3,0.1

Type RM Length L Ch R = 1,30382,1029,1029,1029
BEGIN DESCRIPTION:
Mapping XS 2c42749c
END DESCRIPTION:
XS GIS Cut Line= 4
      1586457.53      6931023.45      1586158.10      6931010.43
      1585788.63      6931033.87      1585385.27      6931368.47
#Sta/Elev= 30
  4697.1 1694.87  4706.1 1694.03  4711.1 1694.65  4789.7 1693.91  4829.8 1692.23
  4859.8 1690.33  4926.7 1689.63  4927.2 1689.13  4932.6 1689.13  4933.1 1689.63
  5130.2 1690.83  5160.2 1691.36  5170.3 1692.04  5195.3 1691.49  5230.4 1691.76
  5300.5 1693.33  5320.6 1692.89  5340.6 1693.20  5354.4 1694.04  5372.6 1694.04
  5400.6 1693.00  5472.2 1692.33  5579.0 1692.80  5657.2 1694.27  5713.1 1694.37
  5748.5 1695.34  5770.5 1693.51  5834.3 1694.03  5855.1 1694.85  5891.1 1694.38
#Mann=3,-1,0
  4697.1    0.05       0  4926.7    0.05       0  4933.1    0.05       0
Bank Sta=4926.7,4933.1
Exp/Cntr=0.3,0.1

Type RM Length L Ch R = 1,29353,160,160,160
BEGIN DESCRIPTION:
Mapping XS 81c9f1a4
END DESCRIPTION:
XS GIS Cut Line= 3
      1586768.78      6930849.85      1586265.30      6930648.45
      1584612.50      6930256.09
#Sta/Elev= 30
  4066.3 1694.61  4109.9 1695.17  4139.5 1694.33  4156.5 1695.49  4223.0 1693.60
  4276.8 1693.47  4318.1 1694.83  4371.9 1694.19  4433.0 1691.86  4462.6 1692.60
  4714.0 1691.21  4714.5 1690.71  4721.5 1691.21  4896.9 1692.39  5060.5 1691.37
  5348.9 1691.40  5413.6 1692.51  5761.5 1692.02  5780.6 1693.22  5821.7 1692.56
  5845.9 1693.50  5972.5 1692.82  6056.9 1695.10  6088.9 1695.44  6104.3 1694.39
  6119.7 1695.83  6188.7 1697.47  6253.3 1697.80  6273.1 1696.69  6307.3 1697.34
#Mann=3,-1,0
  4066.3    0.05       0  4714.0    0.03       0  4721.5    0.05       0
Bank Sta=4714,4721.5
Exp/Cntr=0.3,0.1

Type RM Length L Ch R = 1,29193,518,518,518
BEGIN DESCRIPTION:
Mapping XS 59b2a825
END DESCRIPTION:
XS GIS Cut Line= 3
      1586779.22      6930818.62      1586376.41      6930530.40
      1584568.74      6930124.45
#Sta/Elev= 30
  4116.5 1694.33  4192.1 1694.08  4263.4 1692.03  4292.8 1693.17  4378.8 1692.96
  4399.7 1694.06  4435.4 1692.00  4464.8 1692.03  4571.7 1695.02  4592.6 1697.02
  4654.2 1698.35  4690.7 1697.87  4734.0 1694.70  4782.4 1693.40  4797.7 1694.49
  4874.2 1692.91  4931.0 1694.78  4965.9 1692.78  4972.0 1691.50  5010.6 1690.53
  5011.1 1690.03  5018.1 1690.53  5236.1 1692.74  5361.4 1692.09  5402.4 1693.28
  5781.5 1690.98  5873.3 1692.85  6105.3 1693.29  6181.4 1695.02  6464.5 1697.34
#Mann=3,-1,0
  4116.5    0.05       0  5010.6    0.03       0  5018.1    0.05       0
Bank Sta=5010.6,5018.1
Exp/Cntr=0.3,0.1

Type RM Length L Ch R = 1,28675,557,557,557
BEGIN DESCRIPTION:
Mapping XS 297539fb
END DESCRIPTION:
XS GIS Cut Line= 3
      1586831.28      6930856.80      1586449.33      6930224.84
      1585615.99      6929558.17
#Sta/Elev= 30
  4201.8 1693.74  4242.1 1694.66  4315.8 1692.15  4410.7 1690.94  4475.0 1692.28
  4597.7 1690.61  4643.7 1691.81  4686.4 1690.28  4702.0 1690.31  4737.9 1693.84
  4744.7 1692.90  4750.5 1690.25  4787.4 1688.30  4925.1 1687.90  4972.6 1686.28
  4973.1 1685.78  4980.3 1686.28  5311.0 1687.54  5339.9 1689.27  5360.7 1693.11
  5375.1 1689.69  5403.9 1689.34  5503.1 1689.90  5616.8 1692.76  5645.6 1691.46
  5652.0 1690.02  5695.2 1692.79  5808.9 1695.22  5901.7 1700.76  6007.4 1699.03
#Mann=3,-1,0
  4201.8    0.05       0  4972.6    0.03       0  4980.3    0.05       0
Bank Sta=4972.6,4980.3
Exp/Cntr=0.3,0.1

Type RM Length L Ch R = 1,28118,856,856,856
BEGIN DESCRIPTION:
Mapping XS cdef47a8
END DESCRIPTION:
XS GIS Cut Line= 3
      1587317.39      6931099.86      1586668.08      6929530.40
      1586213.24      6929190.14
#Sta/Elev= 30
  3946.7 1695.13  4018.7 1693.20  4071.9 1693.58  4125.1 1691.76  4186.8 1691.83
  4273.4 1693.17  4303.3 1694.92  4415.1 1697.67  4479.0 1696.78  4510.7 1695.33
  4554.7 1695.40  4684.6 1691.21  4747.5 1692.42  4824.6 1689.16  4994.5 1688.98
  4995.0 1688.48  5002.4 1688.98  5128.3 1691.16  5221.0 1689.33  5333.9 1689.87
  5409.9 1692.16  5505.5 1691.69  5626.1 1694.84  5691.8 1694.11  5785.6 1695.20
  5935.7 1693.03  6041.9 1695.49  6171.2 1696.59  6185.8 1695.69  6213.2 1696.03
#Mann=3,-1,0
  3946.7    0.05       0  4994.5    0.03       0  5002.4    0.05       0
Bank Sta=4994.5,5002.4
Exp/Cntr=0.3,0.1

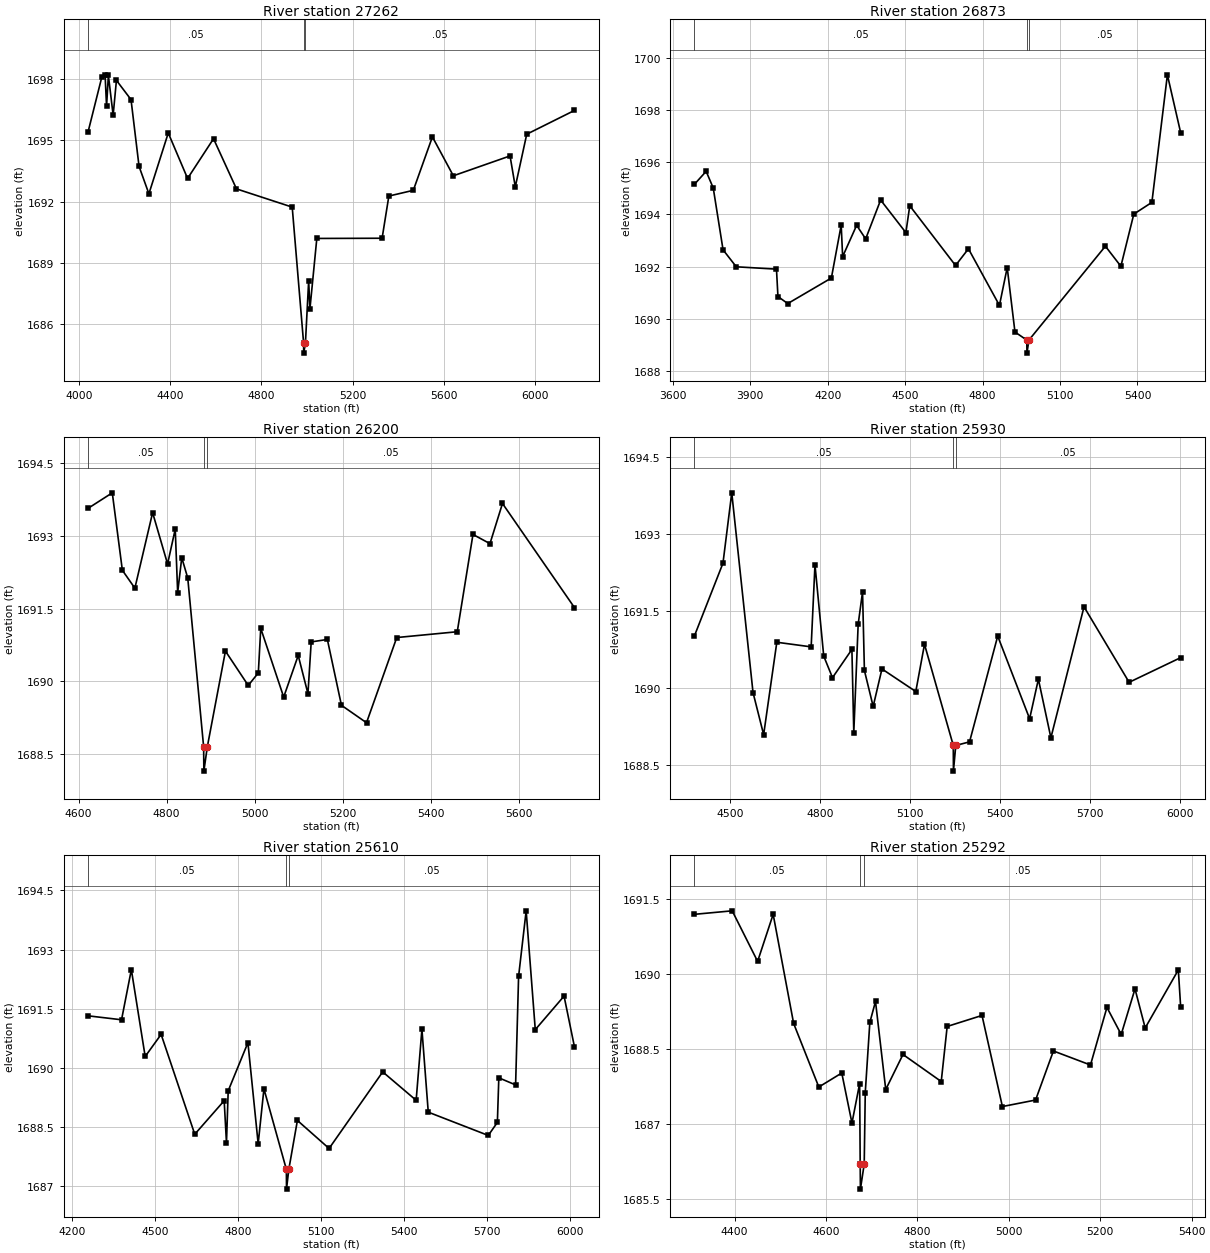
Type RM Length L Ch R = 1,27262,389,389,389
BEGIN DESCRIPTION:
Mapping XS 877f5fe9
END DESCRIPTION:
XS GIS Cut Line= 4
      1588065.70      6930211.56      1587642.77      6929873.16
      1586699.33      6929492.20      1586237.55      6929151.95
#Sta/Elev= 30
  4040.0 1695.41  4100.1 1698.08  4114.5 1698.19  4120.9 1696.65  4128.9 1698.16
  4149.8 1696.22  4164.2 1697.92  4228.2 1696.98  4263.4 1693.72  4306.6 1692.38
  4391.5 1695.35  4476.3 1693.13  4590.0 1695.07  4690.7 1692.62  4935.1 1691.73
  4985.0 1685.10  4985.5 1684.60  4993.1 1685.10  5007.3 1688.14  5012.7 1686.75
  5043.0 1690.20  5329.3 1690.21  5358.9 1692.27  5466.2 1692.55  5549.9 1695.16
  5641.7 1693.26  5890.4 1694.23  5913.4 1692.72  5963.6 1695.29  6172.7 1696.45
#Mann=3,-1,0
  4040.0    0.05       0  4985.0    0.03       0  4993.1    0.05       0
Bank Sta=4985,4993.1
Exp/Cntr=0.3,0.1

Type RM Length L Ch R = 1,26873,673,673,673
BEGIN DESCRIPTION:
Mapping XS f2186a18
END DESCRIPTION:
XS GIS Cut Line= 3
      1588497.59      6929786.24      1587713.38      6929358.62
      1586723.60      6929398.46
#Sta/Elev= 30
  3683.5 1695.15  3729.2 1695.65  3756.7 1695.01  3794.7 1692.64  3845.9 1691.99
  4001.6 1691.90  4007.3 1690.85  4045.3 1690.58  4214.3 1691.56  4252.3 1693.59
  4257.9 1692.38  4312.1 1693.58  4347.1 1693.06  4405.1 1694.55  4502.9 1693.30
  4517.9 1694.33  4695.2 1692.04  4745.2 1692.68  4865.3 1690.51  4895.4 1691.96
  4925.4 1689.49  4971.3 1689.18  4971.8 1688.68  4979.5 1689.18  5275.7 1692.78
  5335.7 1692.01  5385.8 1694.01  5455.8 1694.46  5515.9 1699.35  5567.3 1697.13
#Mann=3,-1,0
  3683.5    0.05       0  4971.3    0.03       0  4979.5    0.05       0
Bank Sta=4971.3,4979.5
Exp/Cntr=0.3,0.1

Type RM Length L Ch R = 1,26200,270,270,270
BEGIN DESCRIPTION:
Mapping XS d4d9dafd
END DESCRIPTION:
XS GIS Cut Line= 2
      1587747.97      6929276.94      1586745.94      6928812.33
#Sta/Elev= 30
  4621.6 1693.57  4676.5 1693.89  4699.4 1692.29  4727.8 1691.92  4768.1 1693.48
  4802.1 1692.42  4819.5 1693.14  4825.0 1691.83  4834.3 1692.55  4847.9 1692.13
  4884.0 1688.64  4884.5 1688.14  4892.3 1688.64  4933.5 1690.62  4985.3 1689.91
  5008.2 1690.17  5013.7 1691.09  5065.8 1689.67  5098.8 1690.53  5120.9 1689.74
  5128.3 1690.81  5165.0 1690.86  5197.0 1689.50  5253.9 1689.14  5322.6 1690.90
  5460.0 1691.02  5495.7 1693.03  5534.3 1692.84  5562.7 1693.67  5726.1 1691.52
#Mann=3,-1,0
  4621.6    0.05       0  4884.0    0.03       0  4892.3    0.05       0
Bank Sta=4884,4892.3
Exp/Cntr=0.3,0.1

Type RM Length L Ch R = 1,25930,320,320,320
BEGIN DESCRIPTION:
Mapping XS d17775b0
END DESCRIPTION:
XS GIS Cut Line= 3
      1587907.65      6929249.14      1586904.98      6928504.48
      1586533.67      6928477.87
#Sta/Elev= 30
  4381.9 1691.02  4477.3 1692.44  4506.6 1693.81  4577.5 1689.92  4612.9 1689.10
  4656.8 1690.90  4771.3 1690.81  4784.0 1692.41  4813.2 1690.63  4842.4 1690.21
  4907.1 1690.76  4913.4 1689.14  4928.0 1691.25  4942.6 1691.88  4948.8 1690.35
  4978.0 1689.65  5007.3 1690.38  5120.1 1689.94  5149.1 1690.86  5245.1 1688.89
  5245.6 1688.39  5253.4 1688.89  5299.3 1688.96  5393.2 1691.02  5499.6 1689.41
  5528.8 1690.18  5570.5 1689.04  5680.9 1691.59  5831.3 1690.12  6003.1 1690.60
#Mann=3,-1,0
  4381.9    0.05       0  5245.1    0.03       0  5253.4    0.05       0
Bank Sta=5245.1,5253.4
Exp/Cntr=0.3,0.1

Type RM Length L Ch R = 1,25610,318,318,318
BEGIN DESCRIPTION:
Mapping XS a8af7af6
END DESCRIPTION:
XS GIS Cut Line= 3
      1588053.49      6929228.30      1587238.93      6928150.11
      1586852.13      6928032.79
#Sta/Elev= 30
  4258.9 1691.32  4379.6 1691.22  4415.0 1692.49  4464.9 1690.29  4522.5 1690.85
  4643.9 1688.32  4750.1 1689.17  4758.4 1688.10  4764.6 1689.42  4835.8 1690.64
  4872.8 1688.08  4893.6 1689.47  4974.6 1687.43  4975.1 1686.93  4983.4 1687.43
  5014.4 1688.67  5128.8 1687.96  5322.4 1689.90  5443.1 1689.18  5463.9 1690.98
  5486.8 1688.88  5703.4 1688.29  5736.3 1688.62  5741.5 1689.75  5802.1 1689.57
  5812.9 1692.32  5840.2 1693.98  5873.1 1690.97  5977.0 1691.82  6014.4 1690.54
#Mann=3,-1,0
  4258.9    0.05       0  4974.6    0.03       0  4983.4    0.05       0
Bank Sta=4974.6,4983.4
Exp/Cntr=0.3,0.1

Type RM Length L Ch R = 1,25292,299,299,299
BEGIN DESCRIPTION:
Mapping XS ec10613d
END DESCRIPTION:
XS GIS Cut Line= 2
      1588164.62      6929151.96      1587686.06      6928201.77
#Sta/Elev= 30
  4312.1 1691.19  4394.9 1691.26  4450.5 1690.25  4484.5 1691.19  4529.3 1689.01
  4584.4 1687.74  4634.6 1688.02  4656.9 1687.02  4673.7 1687.81  4674.9 1686.20
  4675.4 1685.70  4683.7 1686.20  4686.0 1687.63  4696.0 1689.03  4708.4 1689.45
  4730.8 1687.69  4768.5 1688.39  4852.2 1687.85  4865.2 1688.95  4941.4 1689.17
  4986.0 1687.35  5058.6 1687.48  5097.6 1688.46  5178.7 1688.18  5214.7 1689.33
  5245.9 1688.79  5276.1 1689.70  5298.4 1688.92  5370.9 1690.08  5376.0 1689.34
#Mann=3,-1,0
  4312.1    0.05       0  4674.9    0.03       0  4683.7    0.05       0
Bank Sta=4674.9,4683.7
Exp/Cntr=0.3,0.1

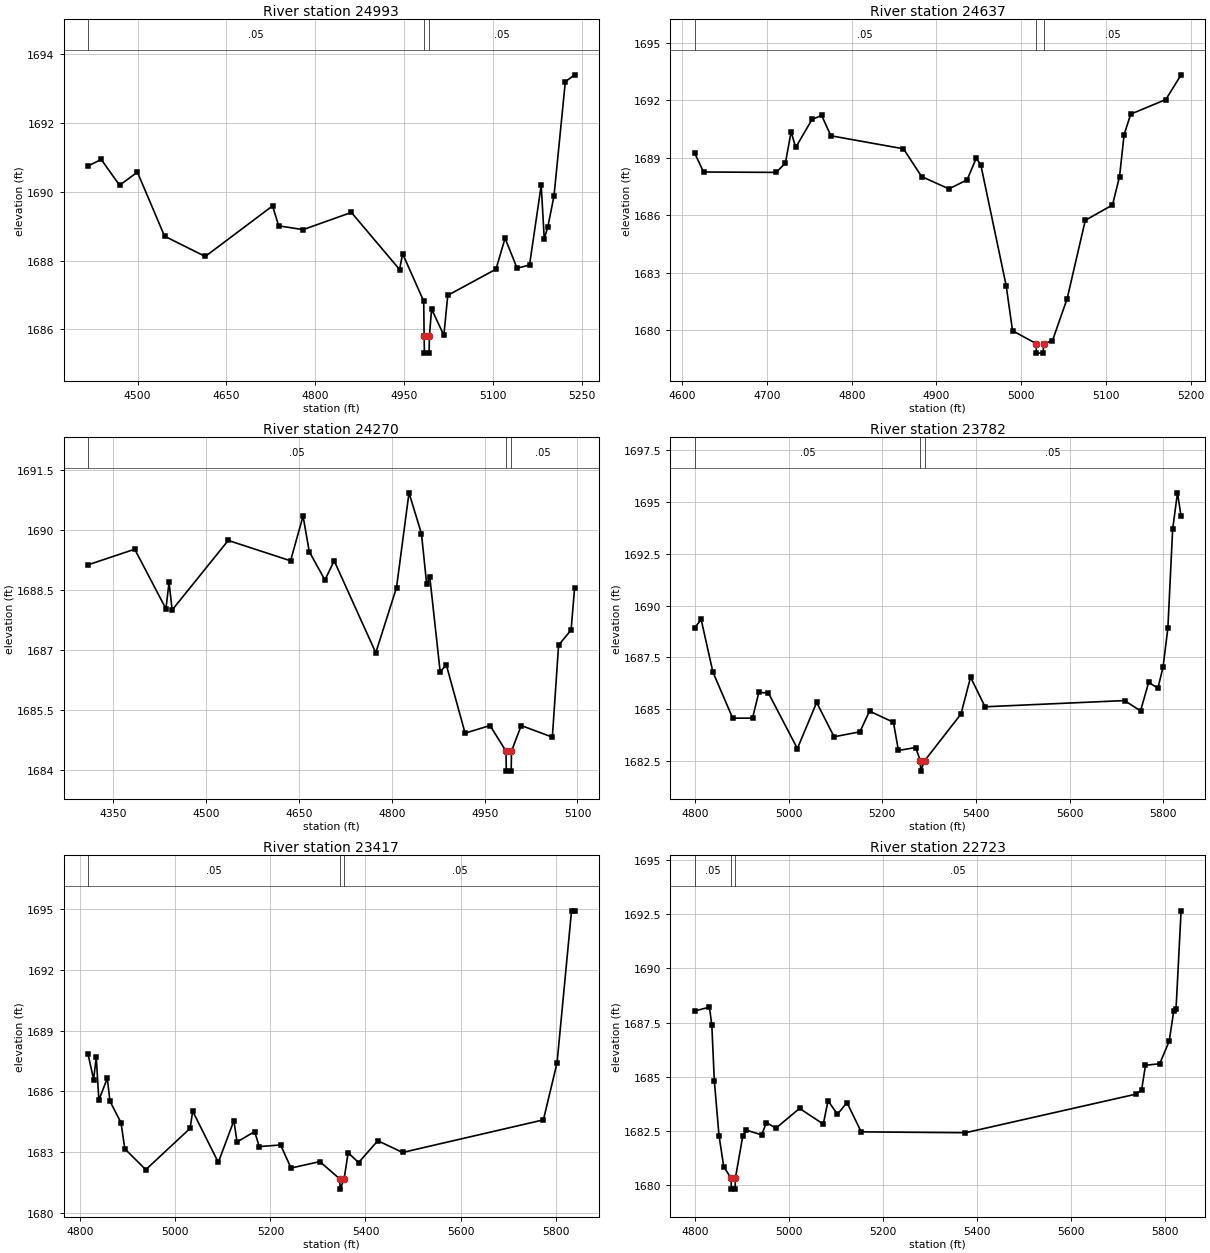
Type RM Length L Ch R = 1,24993,356,356,356
BEGIN DESCRIPTION:
Mapping XS d9264437
END DESCRIPTION:
XS GIS Cut Line= 2
      1588261.83      6929089.41      1588056.97      6928294.28
#Sta/Elev= 30
  4416.6 1690.75  4438.7 1690.94  4469.7 1690.19  4499.8 1690.57  4545.6 1688.71
  4614.3 1688.12  4727.9 1689.59  4738.2 1689.01  4779.5 1688.90  4860.9 1689.40
  4942.3 1687.74  4947.4 1688.20  4983.0 1686.82  4983.7 1685.81  4984.2 1685.31
  4992.1 1685.31  4992.6 1685.81  4996.3 1686.59  5017.0 1685.83  5023.6 1686.99
  5105.0 1687.75  5120.3 1688.65  5140.6 1687.78  5161.6 1687.87  5181.3 1690.19
  5186.4 1688.64  5192.5 1688.98  5202.9 1689.88  5222.0 1693.20  5237.7 1693.40
#Mann=3,-1,0
  4416.6    0.05       0  4983.7    0.03       0  4992.6    0.05       0
Bank Sta=4983.7,4992.6
Exp/Cntr=0.3,0.1

Type RM Length L Ch R = 1,24637,367,367,367
BEGIN DESCRIPTION:
Mapping XS 465cd9f3
END DESCRIPTION:
XS GIS Cut Line= 2
      1588571.52      6928847.88      1588364.91      6928312.57
#Sta/Elev= 30
  4614.7 1689.25  4625.3 1688.26  4711.0 1688.24  4721.8 1688.73  4728.6 1690.36
  4733.9 1689.54  4753.2 1691.00  4764.6 1691.21  4775.4 1690.15  4861.1 1689.47
  4882.5 1688.02  4914.7 1687.38  4936.1 1687.85  4946.8 1688.97  4952.2 1688.65
  4982.2 1682.33  4989.7 1679.98  5017.4 1679.31  5017.9 1678.81  5025.8 1678.81
  5026.3 1679.31  5036.7 1679.45  5054.1 1681.65  5075.5 1685.74  5107.6 1686.54
  5115.9 1688.02  5121.3 1690.21  5129.1 1691.28  5170.5 1692.04  5188.5 1693.33
#Mann=3,-1,0
  4614.7    0.05       0  5017.4    0.03       0  5026.3    0.05       0
Bank Sta=5017.4,5026.3
Exp/Cntr=0.3,0.1

Type RM Length L Ch R = 1,24270,488,488,488
BEGIN DESCRIPTION:
Mapping XS 0a31cf67
END DESCRIPTION:
XS GIS Cut Line= 2
      1588855.58      6929172.80      1588761.92      6928392.30
#Sta/Elev= 30
  4309.3 1689.13  4384.6 1689.52  4435.0 1688.03  4440.1 1688.69  4445.1 1688.00
  4535.7 1689.74  4636.4 1689.23  4656.6 1690.35  4666.6 1689.46  4691.9 1688.75
  4706.9 1689.23  4774.1 1686.93  4807.6 1688.56  4827.8 1690.93  4847.9 1689.91
  4856.4 1688.64  4861.4 1688.82  4878.1 1686.46  4888.2 1686.62  4918.4 1684.92
  4958.7 1685.11  4984.5 1684.47  4985.0 1683.97  4992.9 1683.97  4993.4 1684.47
  5009.1 1685.11  5059.4 1684.82  5069.5 1687.12  5089.7 1687.50  5095.4 1688.56
#Mann=3,-1,0
  4309.3    0.05       0  4984.5    0.03       0  4993.4    0.05       0
Bank Sta=4984.5,4993.4
Exp/Cntr=0.3,0.1

Type RM Length L Ch R = 1,23782,365,365,365
BEGIN DESCRIPTION:
Mapping XS fa82fa92
END DESCRIPTION:
XS GIS Cut Line= 2
      1589398.59      6928471.90      1588387.52      6928232.62
#Sta/Elev= 30
  4799.3 1688.92  4813.3 1689.33  4838.4 1686.79  4880.7 1684.56  4923.0 1684.56
  4936.6 1685.81  4957.1 1685.77  5018.8 1683.09  5060.0 1685.32  5097.2 1683.66
  5152.4 1683.90  5172.9 1684.90  5224.0 1684.36  5234.6 1683.00  5271.4 1683.14
  5281.5 1682.50  5282.0 1682.00  5290.5 1682.50  5368.2 1684.76  5388.7 1686.54
  5419.6 1685.11  5717.6 1685.41  5751.7 1684.91  5769.0 1686.29  5788.8 1686.01
  5799.8 1687.03  5810.1 1688.92  5820.3 1693.70  5830.6 1695.45  5838.3 1694.31
#Mann=3,-1,0
  4799.3    0.05       0  5281.5    0.05       0  5290.5    0.05       0
Bank Sta=5281.5,5290.5
Exp/Cntr=0.3,0.1

Type RM Length L Ch R = 1,23417,694,694,694
BEGIN DESCRIPTION:
Mapping XS b48fdb3f
END DESCRIPTION:
XS GIS Cut Line= 2
      1589445.60      6928189.92      1588509.06      6927776.82
#Sta/Elev= 30
  4816.5 1687.82  4828.1 1686.58  4833.6 1687.69  4839.1 1685.57  4856.9 1686.64
  4862.4 1685.51  4885.7 1684.45  4893.7 1683.16  4937.8 1682.13  5031.1 1684.17
  5036.5 1685.02  5090.4 1682.49  5123.2 1684.55  5129.8 1683.50  5166.9 1684.01
  5176.5 1683.27  5221.5 1683.35  5243.4 1682.21  5304.0 1682.53  5346.1 1681.67
  5346.6 1681.17  5355.1 1681.67  5363.6 1682.97  5385.5 1682.48  5426.0 1683.56
  5478.1 1682.98  5774.4 1684.59  5803.1 1687.40  5833.6 1694.91  5840.1 1694.88
#Mann=3,-1,0
  4816.5    0.05       0  5346.1    0.05       0  5355.1    0.05       0
Bank Sta=5346.1,5355.1
Exp/Cntr=0.3,0.1

Type RM Length L Ch R = 1,22723,464,464,464
BEGIN DESCRIPTION:
Mapping XS 063d8468
END DESCRIPTION:
XS GIS Cut Line= 2
      1589586.60      6927597.80      1588559.90      6927461.53
#Sta/Elev= 30
  4799.4 1688.03  4831.0 1688.21  4836.1 1687.38  4841.4 1684.82  4851.4 1682.29
  4861.5 1680.85  4877.2 1680.32  4877.7 1679.82  4885.7 1679.82  4886.2 1680.32
  4901.9 1682.25  4909.4 1682.54  4942.2 1682.32  4952.3 1682.89  4972.5 1682.63
  5022.9 1683.54  5073.4 1682.82  5083.5 1683.89  5103.6 1683.27  5123.8 1683.81
  5154.1 1682.46  5376.0 1682.42  5739.2 1684.20  5751.1 1684.40  5759.3 1685.53
  5789.6 1685.60  5809.8 1686.64  5819.4 1688.03  5824.4 1688.14  5835.1 1692.65
#Mann=3,-1,0
  4799.4    0.05       0  4877.2    0.05       0  4886.2    0.05       0
Bank Sta=4877.2,4886.2
Exp/Cntr=0.3,0.1

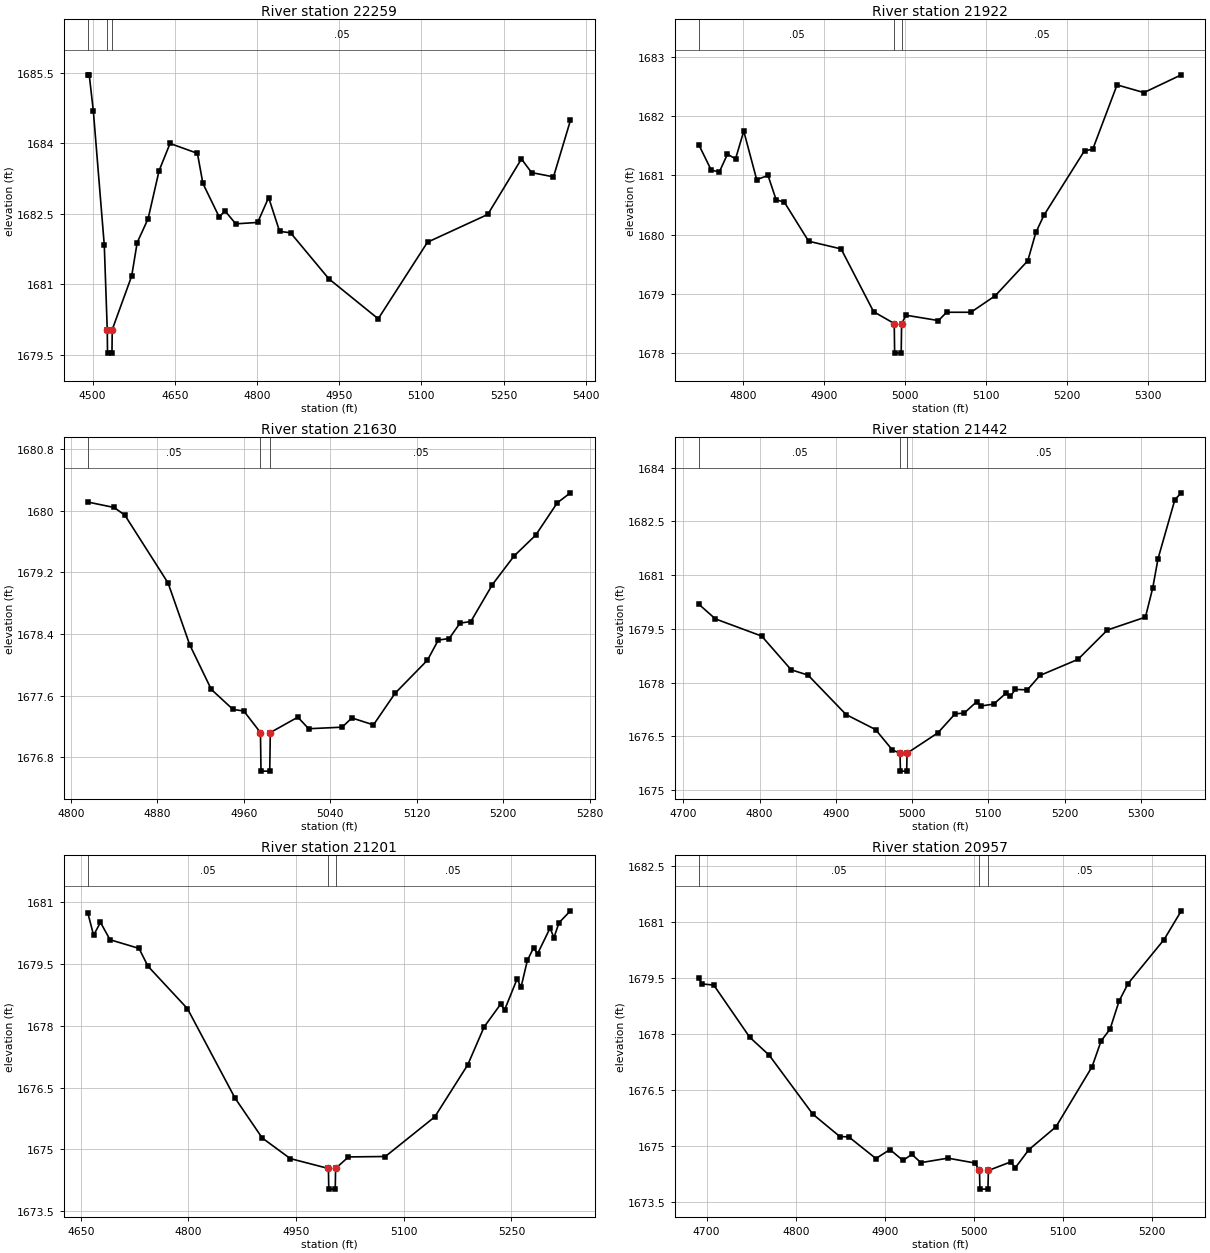
Type RM Length L Ch R = 1,22259,337,337,337
BEGIN DESCRIPTION:
Mapping XS d40e2bb6
END DESCRIPTION:
XS GIS Cut Line= 2
      1589664.85      6927196.43      1588784.08      6927203.77
#Sta/Elev= 30
  4491.3 1685.46  4493.7 1685.46  4501.2 1684.69  4521.2 1681.83  4526.6 1680.04
  4527.1 1679.54  4535.2 1679.54  4535.7 1680.04  4571.2 1681.18  4581.2 1681.89
  4601.2 1682.40  4621.2 1683.42  4641.2 1684.00  4691.2 1683.79  4701.2 1683.15
  4731.2 1682.43  4741.2 1682.57  4761.2 1682.29  4801.2 1682.32  4821.2 1682.85
  4841.2 1682.13  4861.2 1682.10  4931.2 1681.12  5021.2 1680.27  5111.2 1681.90
  5221.2 1682.49  5282.7 1683.67  5301.2 1683.38  5341.2 1683.29  5372.1 1684.49
#Mann=3,-1,0
  4491.3    0.05       0  4526.6   0.035       0  4535.7    0.05       0
Bank Sta=4526.6,4535.7
Exp/Cntr=0.3,0.1

Type RM Length L Ch R = 1,21922,292,292,292
BEGIN DESCRIPTION:
Mapping XS 02386ef2
END DESCRIPTION:
XS GIS Cut Line= 2
      1589450.36      6926897.57      1588855.84      6926859.97
#Sta/Elev= 30
  4745.4 1681.52  4760.8 1681.09  4770.8 1681.06  4780.8 1681.36  4790.8 1681.28
  4800.9 1681.75  4816.9 1680.93  4830.9 1681.00  4840.9 1680.59  4851.0 1680.55
  4881.0 1679.89  4921.1 1679.76  4961.2 1678.70  4986.7 1678.50  4987.2 1678.00
  4995.3 1678.00  4995.8 1678.50  5001.3 1678.64  5041.3 1678.55  5051.4 1678.69
  5081.4 1678.69  5111.5 1678.97  5151.6 1679.56  5161.6 1680.04  5171.6 1680.33
  5221.7 1681.42  5231.7 1681.44  5261.8 1682.53  5295.0 1682.40  5341.1 1682.70
#Mann=3,-1,0
  4745.4    0.05       0  4986.7   0.035       0  4995.8    0.05       0
Bank Sta=4986.7,4995.8
Exp/Cntr=0.3,0.1

Type RM Length L Ch R = 1,21630,188,188,188
BEGIN DESCRIPTION:
Mapping XS 432b2d41
END DESCRIPTION:
XS GIS Cut Line= 2
      1589389.19      6926620.30      1588942.81      6926606.20
#Sta/Elev= 28
  4815.6 1680.11  4839.8 1680.04  4849.8 1679.94  4889.8 1679.06  4909.8 1678.26
  4929.8 1677.68  4949.9 1677.42  4959.9 1677.40  4975.3 1677.12  4975.8 1676.62
  4983.9 1676.62  4984.4 1677.12  5009.9 1677.32  5019.9 1677.17  5050.9 1677.19
  5059.9 1677.31  5079.9 1677.22  5099.9 1677.63  5129.9 1678.06  5139.9 1678.32
  5150.0 1678.34  5160.0 1678.54  5170.0 1678.56  5190.0 1679.04  5210.0 1679.41
  5230.0 1679.68  5250.0 1680.10  5262.2 1680.23
#Mann=3,-1,0
  4815.6    0.05       0  4975.3   0.035       0  4984.4    0.05       0
Bank Sta=4975.3,4984.4
Exp/Cntr=0.3,0.1

Type RM Length L Ch R = 1,21442,241,241,241
BEGIN DESCRIPTION:
Mapping XS 647d7640
END DESCRIPTION:
XS GIS Cut Line= 2
      1589403.34      6926570.96      1588841.73      6926279.58
#Sta/Elev= 30
  4720.3 1680.19  4742.1 1679.78  4802.8 1679.30  4841.4 1678.36  4863.6 1678.21
  4913.4 1677.11  4952.1 1676.69  4974.2 1676.12  4984.2 1676.03  4984.7 1675.53
  4992.9 1675.53  4993.4 1676.03  5033.9 1676.60  5056.4 1677.13  5068.3 1677.15
  5084.8 1677.47  5090.4 1677.35  5106.9 1677.40  5123.4 1677.71  5129.0 1677.62
  5135.3 1677.81  5151.2 1677.80  5167.6 1678.20  5217.5 1678.65  5256.1 1679.47
  5306.0 1679.83  5315.5 1680.64  5322.5 1681.46  5344.6 1683.11  5353.0 1683.30
#Mann=3,-1,0
  4720.3    0.05       0  4984.2   0.035       0  4993.4    0.05       0
Bank Sta=4984.2,4993.4
Exp/Cntr=0.3,0.1

Type RM Length L Ch R = 1,21201,244,244,244
BEGIN DESCRIPTION:
Mapping XS 545e33c3
END DESCRIPTION:
XS GIS Cut Line= 2
      1589431.54      6926563.93      1589149.80      6925953.51
#Sta/Elev= 30
  4659.9 1680.72  4667.8 1680.19  4677.4 1680.50  4690.7 1680.08  4731.1 1679.87
  4743.5 1679.44  4798.6 1678.41  4864.7 1676.25  4902.7 1675.28  4941.8 1674.78
  4995.0 1674.54  4995.5 1674.04  5004.5 1674.04  5005.0 1674.54  5022.9 1674.82
  5074.3 1674.83  5143.2 1675.79  5189.1 1677.05  5212.0 1677.97  5235.0 1678.52
  5240.5 1678.38  5257.9 1679.13  5263.4 1678.93  5272.2 1679.58  5280.8 1679.88
  5286.4 1679.74  5303.8 1680.36  5309.3 1680.13  5316.2 1680.49  5332.2 1680.78
#Mann=3,-1,0
  4659.9    0.05       0  4995.0    0.03       0  5005.0    0.05       0
Bank Sta=4995,5005
Exp/Cntr=0.3,0.1

Type RM Length L Ch R = 1,20957,106,106,106
BEGIN DESCRIPTION:
Mapping XS d164d822
END DESCRIPTION:
XS GIS Cut Line= 2
      1589429.18      6926474.60      1589506.72      6925938.89
#Sta/Elev= 30
  4691.2 1679.49  4694.9 1679.34  4708.0 1679.31  4748.4 1677.91  4770.2 1677.43
  4819.1 1675.85  4849.4 1675.25  4859.5 1675.24  4889.9 1674.66  4905.7 1674.90
  4920.2 1674.61  4930.3 1674.77  4940.4 1674.55  4970.7 1674.67  5001.0 1674.54
  5006.1 1674.34  5006.6 1673.84  5015.6 1673.84  5016.1 1674.34  5041.2 1674.57
  5046.2 1674.41  5061.6 1674.90  5091.9 1675.51  5132.4 1677.12  5142.5 1677.81
  5152.6 1678.13  5162.7 1678.88  5172.8 1679.35  5213.2 1680.53  5232.5 1681.30
#Mann=3,-1,0
  4691.2    0.05       0  5006.1   0.035       0  5016.1    0.05       0
Bank Sta=5006.1,5016.1
Exp/Cntr=0.3,0.1

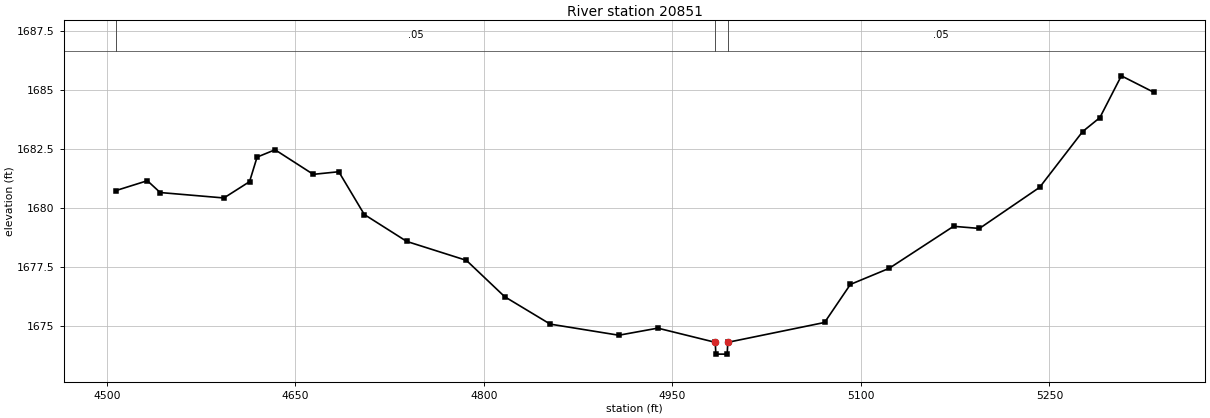
Type RM Length L Ch R = 1,20851,519,519,519
BEGIN DESCRIPTION:
Deadman 07 39.0
END DESCRIPTION:
XS GIS Cut Line= 3
      1589639.46      6926672.87      1589555.00      6926188.00
      1589630.00      6925863.01
#Sta/Elev= 30
  4507.1 1680.74  4532.3 1681.16  4542.5 1680.66  4593.2 1680.43  4613.6 1681.12
  4619.6 1682.16  4633.9 1682.47  4664.3 1681.43  4684.6 1681.54  4704.9 1679.73
  4738.7 1678.59  4786.1 1677.79  4816.6 1676.25  4852.8 1675.09  4907.4 1674.62
  4938.4 1674.92  4984.1 1674.32  4984.6 1673.82  4993.6 1673.82  4994.1 1674.32
  5071.1 1675.16  5091.6 1676.77  5122.4 1677.45  5173.7 1679.23  5194.3 1679.14
  5242.2 1680.88  5276.4 1683.24  5290.1 1683.83  5307.2 1685.60  5332.8 1684.91
#Mann=3,-1,0
  4507.1    0.05       0  4984.1    0.03       0  4994.1    0.05       0
Bank Sta=4984.1,4994.1
Exp/Cntr=0.3,0.1