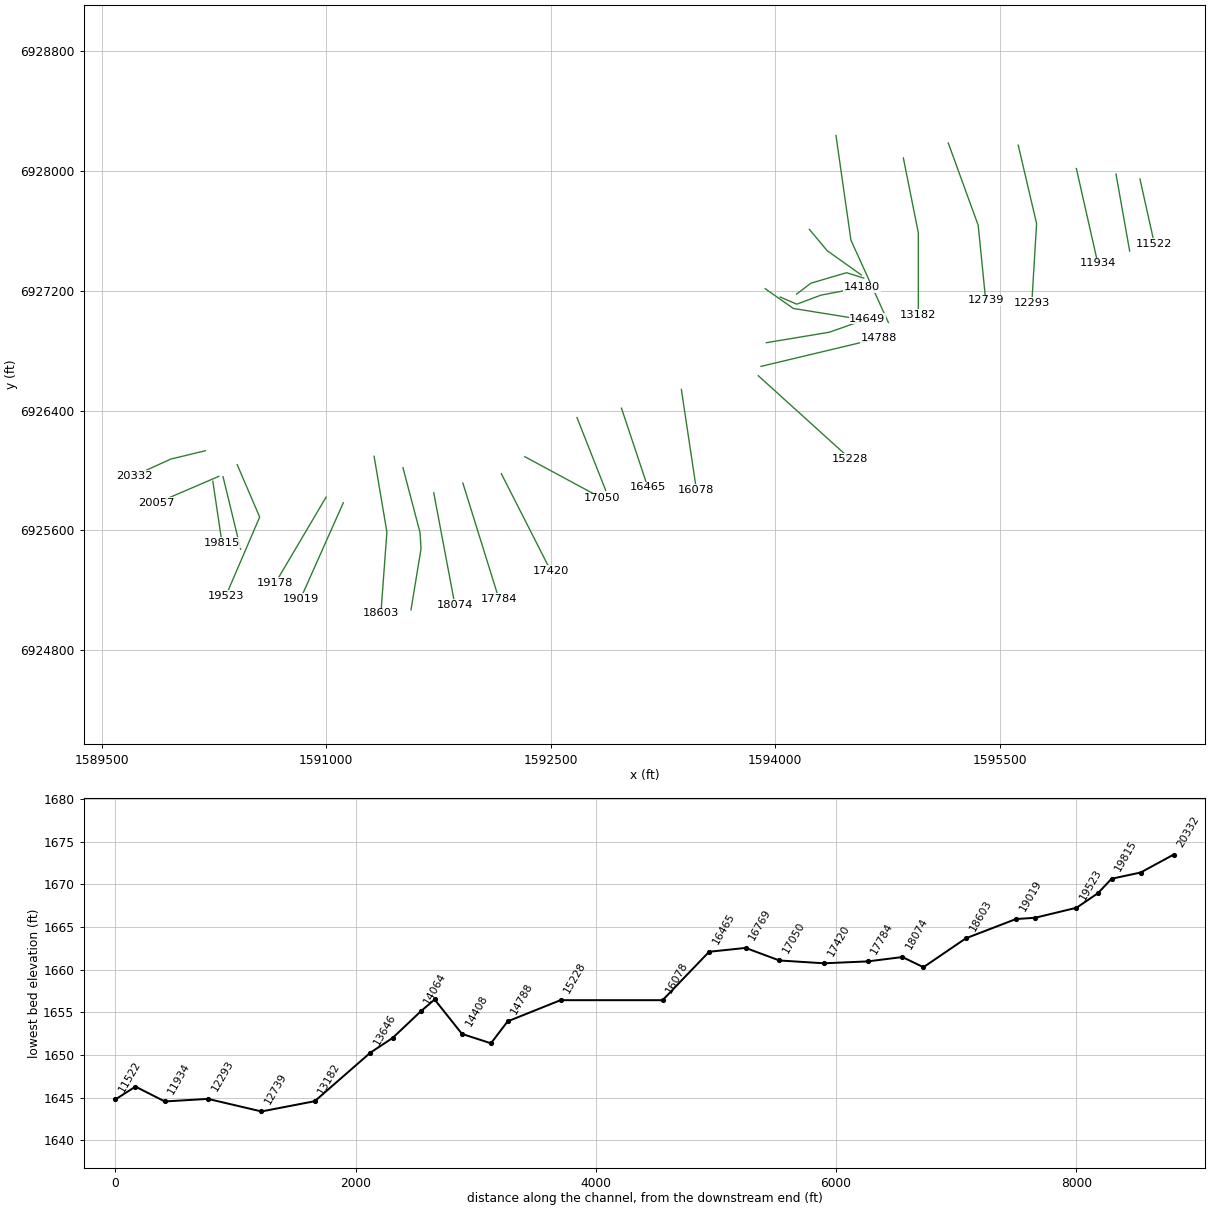
HEC-RAS study Deadman 07.prj: Deadman 07 Base Level Engineering

--- Deadman 07.g01 (geometry) --- (continued)

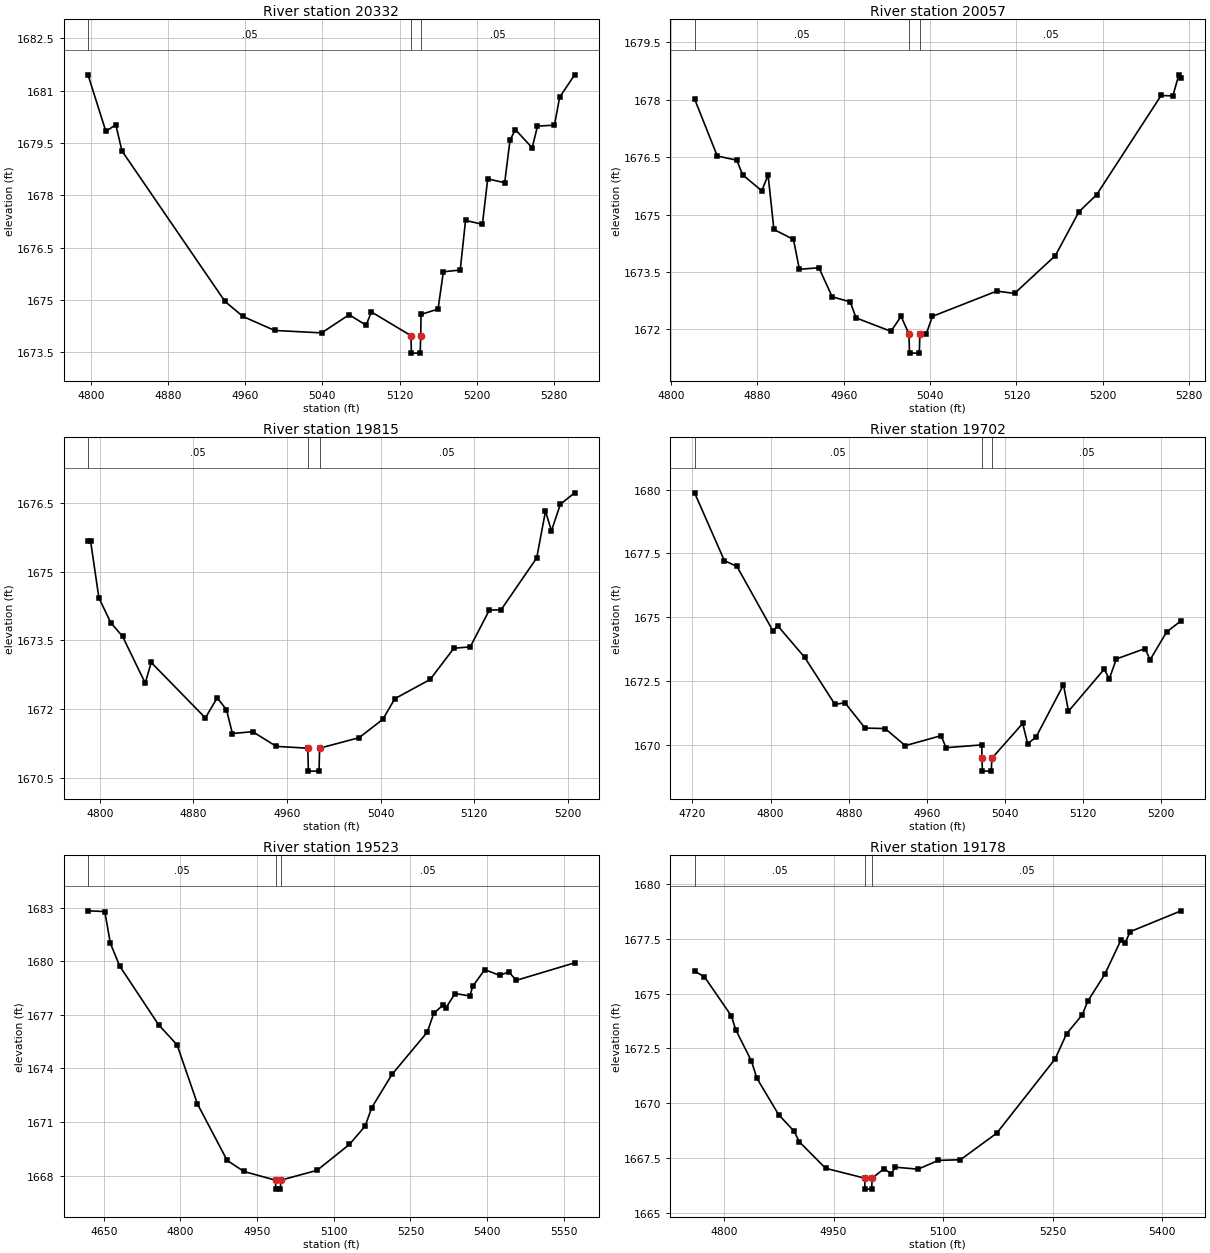
Type RM Length L Ch R = 1,20332,275,275,275
BEGIN DESCRIPTION:
Mapping XS 5869bfa1
END DESCRIPTION:
XS GIS Cut Line= 3
      1590192.86      6926131.55      1589960.22      6926075.15
      1589719.12      6925965.14
#Sta/Elev= 30
  4797.1 1681.44  4815.5 1679.83  4825.8 1680.02  4832.2 1679.27  4939.0 1674.96
  4957.6 1674.53  4990.4 1674.13  5039.2 1674.06  5067.7 1674.58  5085.3 1674.28
  5090.8 1674.66  5131.8 1673.98  5132.3 1673.48  5141.4 1673.48  5141.9 1673.98
  5142.3 1674.59  5159.9 1674.74  5165.4 1675.81  5182.9 1675.86  5188.4 1677.28
  5205.9 1677.17  5211.4 1678.47  5229.0 1678.36  5234.5 1679.58  5240.1 1679.88
  5257.5 1679.36  5263.0 1679.98  5280.6 1680.01  5286.0 1680.81  5301.5 1681.45
#Mann=3,-1,0
  4797.1    0.05       0  5131.8    0.03       0  5141.9    0.05       0
Bank Sta=5131.8,5141.9
Exp/Cntr=0.3,0.1

Type RM Length L Ch R = 1,20057,242,242,242
BEGIN DESCRIPTION:
Mapping XS 9cca8f94
END DESCRIPTION:
XS GIS Cut Line= 2
      1590282.16      6925960.03      1589868.02      6925782.20
#Sta/Elev= 30
  4821.8 1678.02  4842.8 1676.53  4860.9 1676.42  4866.3 1676.04  4884.0 1675.62
  4889.9 1676.03  4895.3 1674.61  4913.4 1674.35  4918.9 1673.57  4937.0 1673.61
  4949.3 1672.85  4966.0 1672.72  4971.4 1672.30  5003.7 1671.95  5013.1 1672.34
  5020.4 1671.88  5020.9 1671.38  5030.0 1671.38  5030.5 1671.88  5036.4 1671.88
  5042.1 1672.34  5101.7 1673.00  5118.2 1672.94  5156.1 1673.93  5177.8 1675.07
  5194.3 1675.52  5254.0 1678.11  5264.9 1678.10  5270.4 1678.65  5272.5 1678.56
#Mann=3,-1,0
  4821.8    0.05       0  5020.4    0.03       0  5030.5    0.05       0
Bank Sta=5020.4,5030.5
Exp/Cntr=0.3,0.1

Type RM Length L Ch R = 1,19815,113,113,113
BEGIN DESCRIPTION:
Mapping XS 7cbd9e5d
END DESCRIPTION:
XS GIS Cut Line= 2
      1590242.20      6925927.09      1590303.29      6925515.91
#Sta/Elev= 30
  4790.0 1675.67  4792.1 1675.67  4799.2 1674.43  4809.3 1673.89  4819.4 1673.59
  4838.8 1672.57  4843.9 1673.02  4890.2 1671.81  4900.3 1672.25  4908.2 1671.99
  4913.3 1671.47  4930.6 1671.51  4950.8 1671.19  4977.7 1671.15  4978.2 1670.65
  4987.3 1670.65  4987.8 1671.15  5021.6 1671.38  5041.8 1671.78  5052.1 1672.23
  5082.3 1672.65  5102.5 1673.33  5116.5 1673.36  5132.8 1674.16  5142.9 1674.17
  5173.3 1675.30  5180.8 1676.32  5185.9 1675.89  5193.5 1676.47  5205.7 1676.72
#Mann=3,-1,0
  4790.0    0.05       0  4977.7    0.03       0  4987.8    0.05       0
Bank Sta=4977.7,4987.8
Exp/Cntr=0.3,0.1

Type RM Length L Ch R = 1,19702,179,179,179
BEGIN DESCRIPTION:
Mapping XS 6802f447
END DESCRIPTION:
XS GIS Cut Line= 2
      1590310.35      6925957.62      1590427.83      6925473.58
#Sta/Elev= 30
  4722.2 1679.88  4752.7 1677.22  4765.6 1676.99  4802.3 1674.47  4807.4 1674.66
  4835.0 1673.42  4865.9 1671.58  4876.2 1671.64  4896.7 1670.65  4917.3 1670.63
  4937.9 1669.96  4974.5 1670.35  4979.7 1669.88  5016.3 1669.99  5016.4 1669.46
  5016.9 1668.96  5026.0 1668.96  5026.5 1669.46  5058.1 1670.83  5063.2 1670.04
  5071.7 1670.29  5099.9 1672.35  5105.0 1671.31  5141.6 1672.96  5146.8 1672.58
  5154.0 1673.36  5183.4 1673.77  5188.6 1673.33  5205.5 1674.42  5220.3 1674.86
#Mann=3,-1,0
  4722.2    0.05       0  5016.4    0.03       0  5026.5    0.05       0
Bank Sta=5016.4,5026.5
Exp/Cntr=0.3,0.1

Type RM Length L Ch R = 1,19523,345,345,345
BEGIN DESCRIPTION:
Deadman 07 38.0
END DESCRIPTION:
XS GIS Cut Line= 3
      1590405.01      6926037.98      1590555.00      6925688.00
      1590329.98      6925162.96
#Sta/Elev= 30
  4619.3 1682.82  4651.9 1682.78  4662.8 1681.01  4680.9 1679.74  4757.1 1676.45
  4793.4 1675.32  4833.2 1672.02  4891.3 1668.86  4923.9 1668.24  4986.0 1667.75
  4986.5 1667.25  4995.6 1667.25  4996.1 1667.75  5067.2 1668.30  5130.6 1669.75
  5161.5 1670.78  5174.1 1671.80  5214.0 1673.67  5282.9 1676.03  5295.6 1677.08
  5313.8 1677.55  5319.2 1677.38  5337.3 1678.19  5366.4 1678.06  5371.8 1678.59
  5395.4 1679.53  5424.4 1679.21  5442.5 1679.40  5457.0 1678.93  5571.3 1679.91
#Mann=3,-1,0
  4619.3    0.05       0  4986.0    0.05       0  4996.1    0.05       0
Bank Sta=4986,4996.1
Exp/Cntr=0.3,0.1

Type RM Length L Ch R = 1,19178,159,159,159
BEGIN DESCRIPTION:
Mapping XS a1bdc9a3
END DESCRIPTION:
XS GIS Cut Line= 2
      1590998.79      6925821.34      1590660.45      6925248.04
#Sta/Elev= 30
  4759.9 1676.02  4773.4 1675.76  4810.2 1673.98  4816.3 1673.34  4837.7 1671.92
  4845.1 1671.14  4874.8 1669.48  4896.3 1668.71  4903.1 1668.24  4939.2 1667.03
  4992.6 1666.58  4993.1 1666.08  5002.3 1666.08  5002.8 1666.58  5019.2 1667.01
  5029.0 1666.78  5034.8 1667.08  5065.7 1666.99  5093.4 1667.39  5123.7 1667.42
  5173.3 1668.63  5253.3 1672.02  5269.0 1673.17  5290.4 1674.03  5297.9 1674.65
  5321.1 1675.87  5343.2 1677.43  5349.0 1677.31  5356.0 1677.82  5425.6 1678.77
#Mann=3,-1,0
  4759.9    0.05       0  4992.6    0.05       0  5002.8    0.05       0
Bank Sta=4992.6,5002.8
Exp/Cntr=0.3,0.1

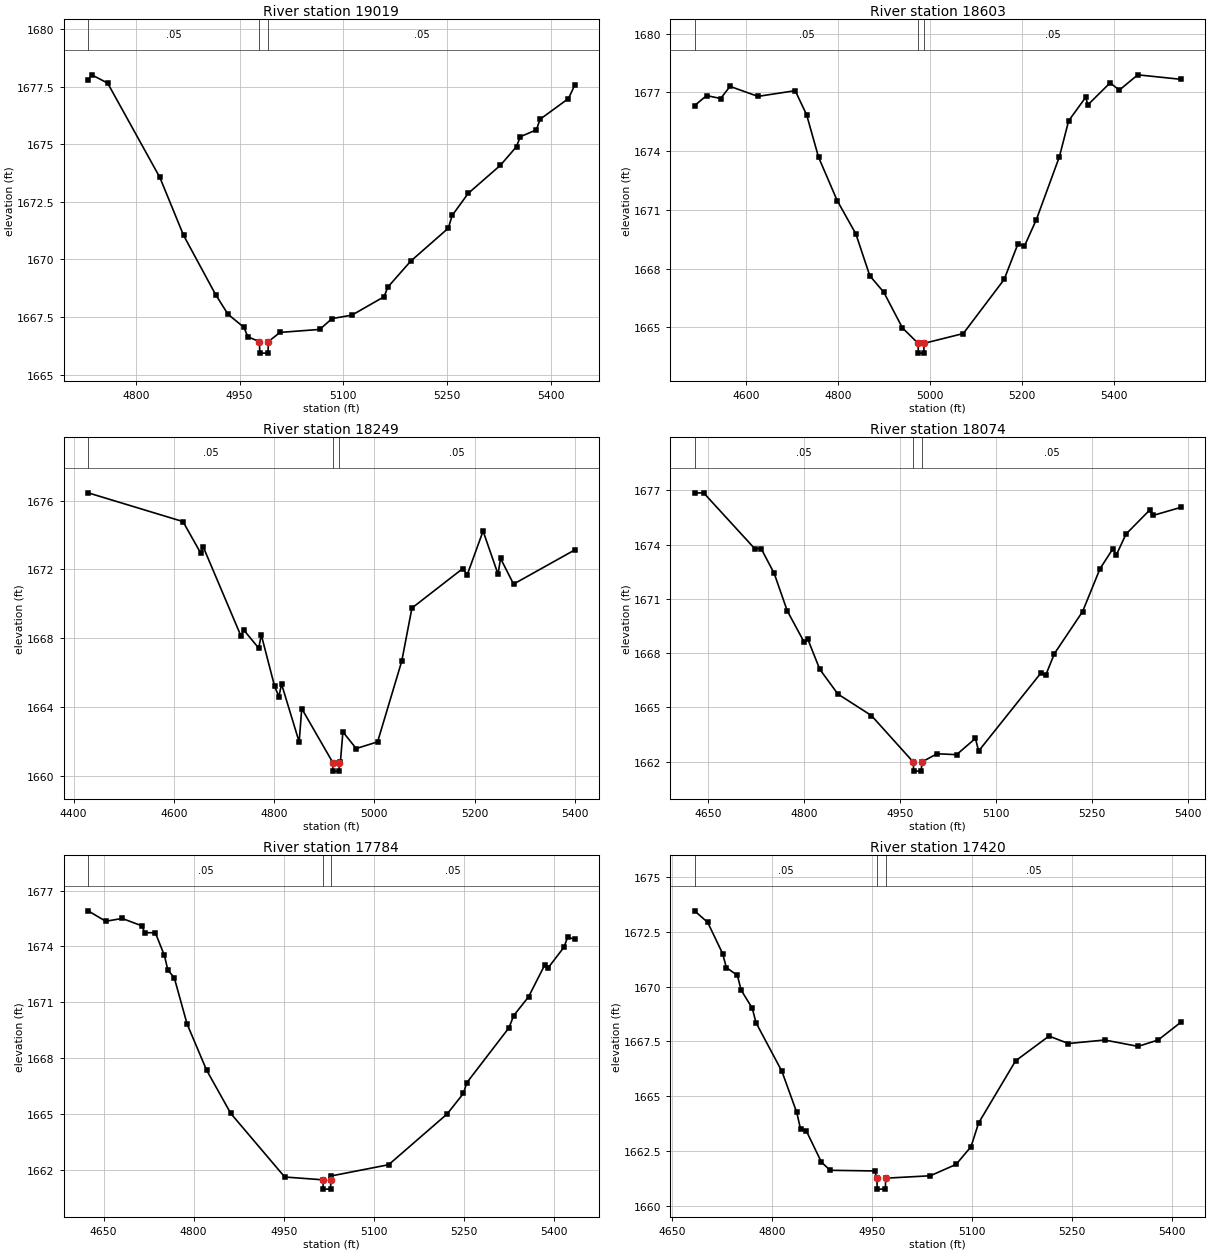
Type RM Length L Ch R = 1,19019,416,416,416
BEGIN DESCRIPTION:
Mapping XS 34eee3c5
END DESCRIPTION:
XS GIS Cut Line= 2
      1591113.93      6925783.74      1590827.94      6925141.43
#Sta/Elev= 30
  4731.1 1677.79  4736.3 1678.02  4759.3 1677.66  4834.8 1673.56  4869.0 1671.05
  4915.4 1668.47  4933.2 1667.62  4956.3 1667.05  4961.9 1666.64  4978.7 1666.43
  4979.2 1665.93  4991.1 1665.93  4991.6 1666.43  5008.4 1666.83  5065.8 1666.96
  5083.6 1667.43  5112.3 1667.58  5158.8 1668.38  5164.3 1668.80  5197.1 1669.92
  5251.7 1671.36  5257.2 1671.91  5280.4 1672.87  5326.9 1674.09  5350.2 1674.90
  5355.6 1675.33  5378.9 1675.63  5384.3 1676.09  5425.3 1676.99  5434.2 1677.56
#Mann=3,-1,0
  4731.1    0.05       0  4978.7    0.03       0  4991.6    0.05       0
Bank Sta=4978.7,4991.6
Exp/Cntr=0.3,0.1

Type RM Length L Ch R = 1,18603,354,354,354
BEGIN DESCRIPTION:
Deadman 07 37.0
END DESCRIPTION:
XS GIS Cut Line= 3
      1591319.45      6926093.98      1591405.00      6925588.00
      1591364.86      6925043.93
#Sta/Elev= 30
  4487.2 1676.32  4513.5 1676.83  4544.0 1676.68  4564.3 1677.30  4625.1 1676.79
  4706.2 1677.08  4731.0 1675.85  4756.9 1673.69  4797.5 1671.47  4838.1 1669.77
  4868.5 1667.63  4898.9 1666.79  4939.5 1664.97  4973.6 1664.18  4974.1 1663.68
  4986.0 1663.68  4986.5 1664.18  5071.9 1664.68  5160.8 1667.44  5190.9 1669.26
  5205.1 1669.15  5231.0 1670.50  5281.1 1673.71  5301.2 1675.54  5338.2 1676.74
  5343.2 1676.36  5391.4 1677.48  5411.5 1677.11  5451.6 1677.89  5545.9 1677.66
#Mann=3,-1,0
  4487.2    0.05       0  4973.6    0.05       0  4986.5    0.05       0
Bank Sta=4973.6,4986.5
Exp/Cntr=0.3,0.1

Type RM Length L Ch R = 1,18249,175,175,175
BEGIN DESCRIPTION:
Mapping XS 503088d3
END DESCRIPTION:
XS GIS Cut Line= 4
      1591512.36      6926017.77      1591626.36      6925584.11
      1591633.06      6925476.82      1591566.01      6925067.77
#Sta/Elev= 30
  4428.9 1676.45  4618.1 1674.78  4653.3 1672.96  4658.5 1673.31  4734.0 1668.12
  4739.2 1668.49  4769.2 1667.43  4774.3 1668.20  4800.9 1665.21  4809.5 1664.62
  4814.7 1665.35  4849.9 1661.98  4855.0 1663.92  4916.9 1660.79  4917.4 1660.29
  4929.5 1660.29  4930.0 1660.79  4932.1 1660.82  4937.1 1662.57  4963.6 1661.60
  5006.3 1661.99  5054.5 1666.68  5074.8 1669.76  5176.1 1672.05  5185.2 1671.70
  5216.7 1674.23  5246.5 1671.73  5251.6 1672.64  5277.5 1671.15  5399.3 1673.13
#Mann=3,-1,0
  4428.9    0.05       0  4916.9    0.05       0  4930.0    0.05       0
Bank Sta=4916.9,4930
Exp/Cntr=0.3,0.1

Type RM Length L Ch R = 1,18074,290,290,290
BEGIN DESCRIPTION:
Mapping XS 56138763
END DESCRIPTION:
XS GIS Cut Line= 2
      1591717.99      6925850.14      1591858.82      6925103.51
#Sta/Elev= 30
  4629.3 1676.85  4643.4 1676.86  4723.1 1673.78  4733.2 1673.78  4753.6 1672.41
  4774.0 1670.34  4800.7 1668.59  4805.8 1668.80  4824.8 1667.11  4853.1 1665.74
  4905.5 1664.55  4970.9 1661.98  4971.4 1661.48  4983.5 1661.48  4984.0 1661.98
  5008.0 1662.44  5038.5 1662.39  5067.9 1663.29  5072.9 1662.59  5170.8 1666.93
  5177.8 1666.79  5191.2 1667.97  5235.3 1670.30  5262.4 1672.66  5282.6 1673.77
  5287.7 1673.41  5303.1 1674.58  5340.1 1675.91  5345.2 1675.61  5389.1 1676.06
#Mann=3,-1,0
  4629.3    0.05       0  4970.9    0.05       0  4984.0    0.05       0
Bank Sta=4970.9,4984
Exp/Cntr=0.3,0.1

Type RM Length L Ch R = 1,17784,364,364,364
BEGIN DESCRIPTION:
Mapping XS eca2b0a9
END DESCRIPTION:
XS GIS Cut Line= 2
      1591912.46      6925914.93      1592153.29      6925141.14
#Sta/Elev= 30
  4624.3 1675.91  4653.7 1675.35  4681.0 1675.50  4713.5 1675.11  4718.8 1674.74
  4736.3 1674.73  4751.3 1673.52  4757.2 1672.72  4767.7 1672.33  4789.1 1669.84
  4821.6 1667.36  4862.0 1665.03  4951.8 1661.62  5015.5 1661.47  5016.0 1660.97
  5028.1 1660.97  5028.6 1661.47  5029.5 1661.68  5124.9 1662.28  5222.5 1665.01
  5249.5 1666.11  5255.0 1666.68  5325.3 1669.63  5333.3 1670.29  5357.9 1671.29
  5385.2 1673.02  5390.4 1672.84  5417.0 1673.96  5422.9 1674.48  5434.7 1674.40
#Mann=3,-1,0
  4624.3    0.05       0  5015.5    0.05       0  5028.6    0.05       0
Bank Sta=5015.5,5028.6
Exp/Cntr=0.3,0.1

Type RM Length L Ch R = 1,17420,370,370,370
BEGIN DESCRIPTION:
Mapping XS 79d3e6fe
END DESCRIPTION:
XS GIS Cut Line= 2
      1592169.51      6925977.50      1592500.17      6925327.36
#Sta/Elev= 30
  4684.1 1673.46  4703.8 1672.93  4726.1 1671.51  4731.7 1670.87  4748.3 1670.51
  4753.9 1669.84  4770.6 1669.01  4776.2 1668.35  4815.0 1666.13  4837.3 1664.25
  4842.9 1663.50  4851.8 1663.40  4874.3 1661.98  4887.4 1661.61  4954.1 1661.58
  4957.4 1661.25  4957.9 1660.75  4970.1 1660.75  4970.6 1661.25  5037.5 1661.36
  5076.2 1661.88  5098.6 1662.69  5109.9 1663.77  5165.4 1666.61  5215.5 1667.74
  5244.5 1667.40  5298.9 1667.56  5349.0 1667.27  5379.1 1667.56  5413.5 1668.38
#Mann=3,-1,0
  4684.1    0.05       0  4957.4    0.03       0  4970.6    0.05       0
Bank Sta=4957.4,4970.6
Exp/Cntr=0.3,0.1

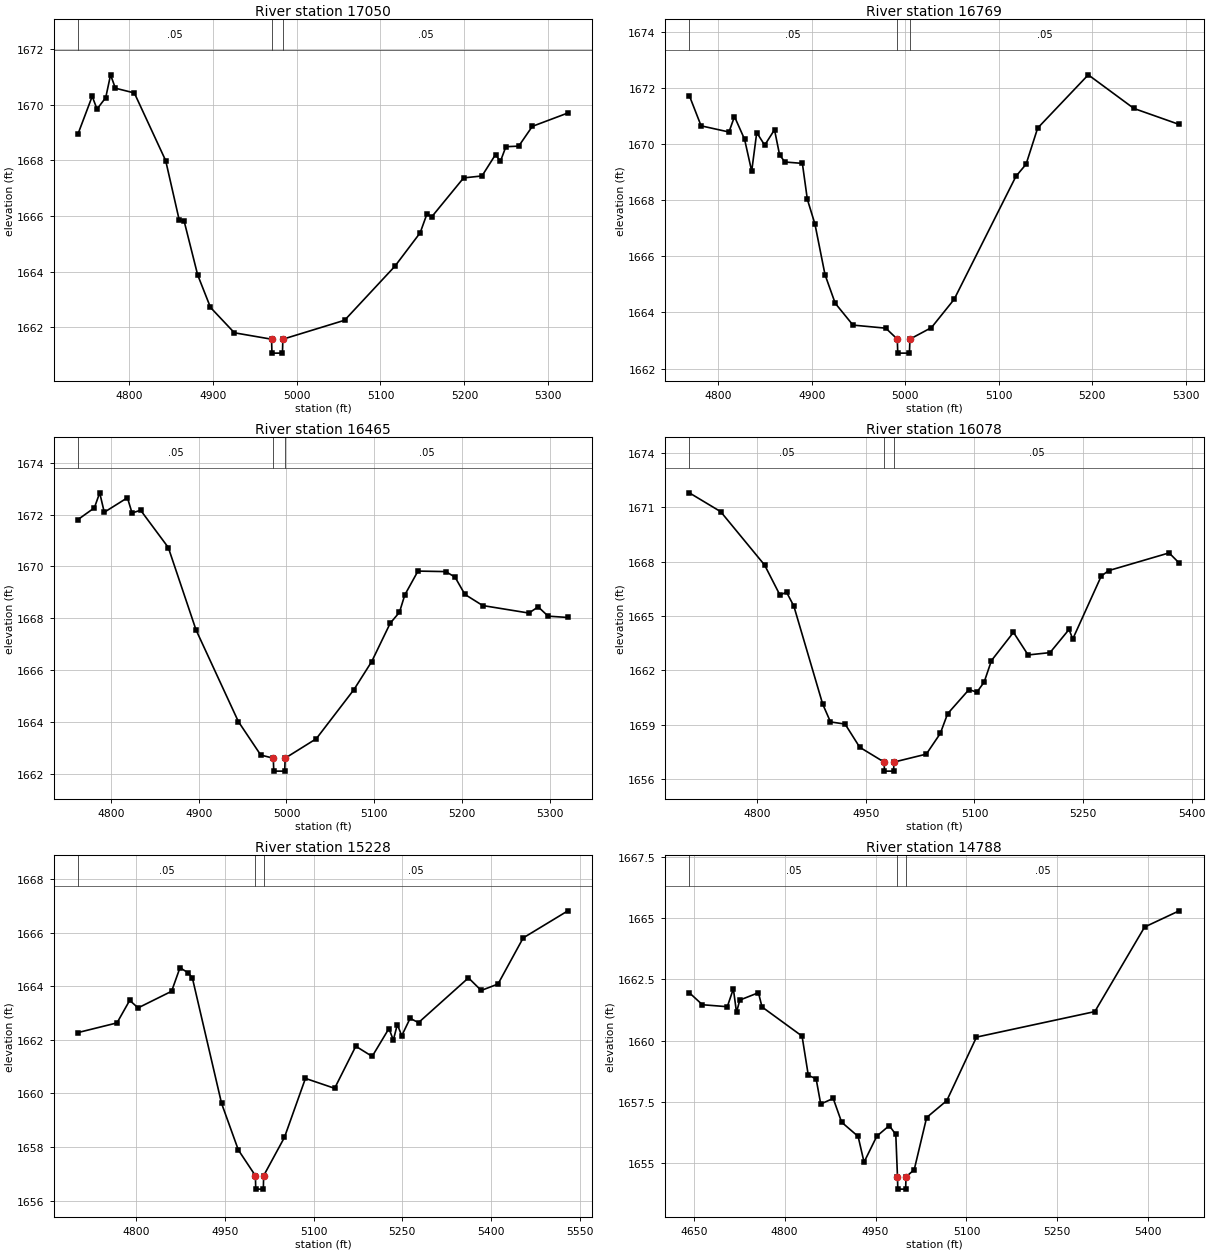
Type RM Length L Ch R = 1,17050,281,281,281
BEGIN DESCRIPTION:
Mapping XS 8881fa6f
END DESCRIPTION:
XS GIS Cut Line= 2
      1592325.97      6926091.50      1592840.03      6925814.36
#Sta/Elev= 30
  4739.4 1668.95  4756.3 1670.30  4762.0 1669.84  4772.4 1670.25  4778.2 1671.07
  4783.9 1670.59  4806.5 1670.42  4843.9 1667.99  4860.1 1665.85  4865.8 1665.83
  4882.0 1663.89  4897.3 1662.72  4925.8 1661.81  4970.1 1661.58  4970.6 1661.08
  4983.1 1661.08  4983.6 1661.58  5057.2 1662.26  5117.2 1664.20  5147.3 1665.40
  5155.3 1666.07  5161.0 1665.97  5199.1 1667.37  5221.0 1667.44  5237.2 1668.21
  5242.9 1667.96  5249.5 1668.49  5264.8 1668.51  5281.0 1669.22  5323.4 1669.70
#Mann=3,-1,0
  4739.4    0.05       0  4970.1    0.05       0  4983.6    0.05       0
Bank Sta=4970.1,4983.6
Exp/Cntr=0.3,0.1

Type RM Length L Ch R = 1,16769,304,304,304
BEGIN DESCRIPTION:
Mapping XS 8a681db1
END DESCRIPTION:
XS GIS Cut Line= 2
      1592674.68      6926352.97      1592866.90      6925865.71
#Sta/Elev= 30
  4769.0 1671.74  4781.6 1670.66  4811.4 1670.44  4817.3 1670.99  4828.1 1670.18
  4835.7 1669.04  4841.1 1670.42  4849.6 1669.97  4860.1 1670.52  4865.5 1669.63
  4871.1 1669.37  4889.9 1669.32  4895.2 1668.04  4903.3 1667.16  4914.1 1665.35
  4925.0 1664.33  4944.0 1663.55  4979.1 1663.44  4991.4 1663.05  4991.9 1662.55
  5004.4 1662.55  5004.9 1663.05  5027.9 1663.46  5052.2 1664.47  5118.3 1668.86
  5129.1 1669.29  5141.5 1670.58  5195.6 1672.48  5244.4 1671.28  5292.8 1670.71
#Mann=3,-1,0
  4769.0    0.05       0  4991.4    0.05       0  5004.9    0.05       0
Bank Sta=4991.4,5004.9
Exp/Cntr=0.3,0.1

Type RM Length L Ch R = 1,16465,387,387,387
BEGIN DESCRIPTION:
Mapping XS 2ed324f9
END DESCRIPTION:
XS GIS Cut Line= 2
      1592971.93      6926415.63      1593148.52      6925885.88
#Sta/Elev= 30
  4762.4 1671.81  4781.0 1672.26  4787.1 1672.84  4792.3 1672.09  4818.7 1672.65
  4824.0 1672.06  4833.7 1672.17  4865.3 1670.73  4896.9 1667.55  4945.2 1664.01
  4970.7 1662.72  4985.0 1662.60  4985.5 1662.10  4998.0 1662.10  4998.5 1662.60
  5034.0 1663.35  5077.0 1665.25  5097.2 1666.33  5118.3 1667.81  5128.8 1668.23
  5134.9 1668.90  5149.9 1669.82  5181.5 1669.80  5192.1 1669.59  5203.4 1668.92
  5223.7 1668.49  5276.4 1668.20  5286.9 1668.44  5298.3 1668.08  5320.8 1668.03
#Mann=3,-1,0
  4762.4    0.05       0  4985.0    0.03       0  4998.5    0.05       0
Bank Sta=4985,4998.5
Exp/Cntr=0.3,0.1

Type RM Length L Ch R = 1,16078,850,850,850
BEGIN DESCRIPTION:
Mapping XS aebe2b12
END DESCRIPTION:
XS GIS Cut Line= 2
      1593372.04      6926540.82      1593472.42      6925871.60
#Sta/Elev= 30
  4706.1 1671.81  4749.4 1670.77  4810.1 1667.82  4831.3 1666.16  4840.4 1666.32
  4850.5 1665.55  4890.3 1660.14  4901.1 1659.15  4921.3 1659.03  4941.5 1657.75
  4975.2 1656.93  4975.7 1656.43  4988.3 1656.43  4988.8 1656.93  5033.5 1657.37
  5052.8 1658.51  5062.9 1659.60  5092.5 1660.94  5103.3 1660.79  5113.4 1661.35
  5123.5 1662.54  5153.9 1664.10  5174.1 1662.85  5204.4 1662.98  5230.7 1664.26
  5235.8 1663.73  5275.2 1667.21  5285.3 1667.51  5368.9 1668.49  5382.8 1667.93
#Mann=3,-1,0
  4706.1    0.05       0  4975.2    0.05       0  4988.8    0.05       0
Bank Sta=4975.2,4988.8
Exp/Cntr=0.3,0.1

Type RM Length L Ch R = 1,15228,440,440,440
BEGIN DESCRIPTION:
Mapping XS 494bc946
END DESCRIPTION:
XS GIS Cut Line= 2
      1593886.11      6926632.43      1594500.41      6926076.21
#Sta/Elev= 30
  4701.3 1662.27  4767.2 1662.63  4788.7 1663.47  4802.9 1663.19  4859.6 1663.81
  4873.8 1664.69  4888.0 1664.49  4894.8 1664.30  4944.1 1659.63  4972.5 1657.89
  5001.4 1656.93  5001.9 1656.43  5014.8 1656.43  5015.3 1656.93  5050.5 1658.36
  5086.0 1660.56  5135.4 1660.19  5171.2 1661.76  5198.9 1661.38  5227.3 1662.42
  5234.7 1661.99  5241.5 1662.57  5248.9 1662.15  5263.1 1662.80  5277.3 1662.64
  5361.8 1664.31  5383.4 1663.84  5411.8 1664.08  5454.4 1665.80  5530.0 1666.81
#Mann=3,-1,0
  4701.3    0.05       0  5001.4    0.03       0  5015.3    0.05       0
Bank Sta=5001.4,5015.3
Exp/Cntr=0.3,0.1

Type RM Length L Ch R = 1,14788,139,139,139
BEGIN DESCRIPTION:
Mapping XS b651afee
END DESCRIPTION:
XS GIS Cut Line= 2
      1593903.98      6926694.99      1594690.40      6926882.66
#Sta/Elev= 30
  4642.6 1661.96  4664.2 1661.47  4705.3 1661.39  4715.3 1662.12  4720.5 1661.16
  4725.9 1661.66  4756.7 1661.96  4762.6 1661.38  4828.7 1660.19  4839.0 1658.59
  4851.9 1658.45  4859.5 1657.42  4880.1 1657.65  4894.0 1656.68  4921.2 1656.10
  4931.0 1655.05  4952.1 1656.11  4972.6 1656.54  4983.4 1656.18  4986.2 1654.45
  4986.7 1653.95  4999.7 1653.95  5000.2 1654.45  5013.8 1654.74  5034.3 1656.87
  5067.6 1657.56  5116.6 1660.15  5311.9 1661.19  5394.1 1664.64  5451.1 1665.30
#Mann=3,-1,0
  4642.6    0.05       0  4986.2    0.03       0  5000.2    0.05       0
Bank Sta=4986.2,5000.2
Exp/Cntr=0.3,0.1

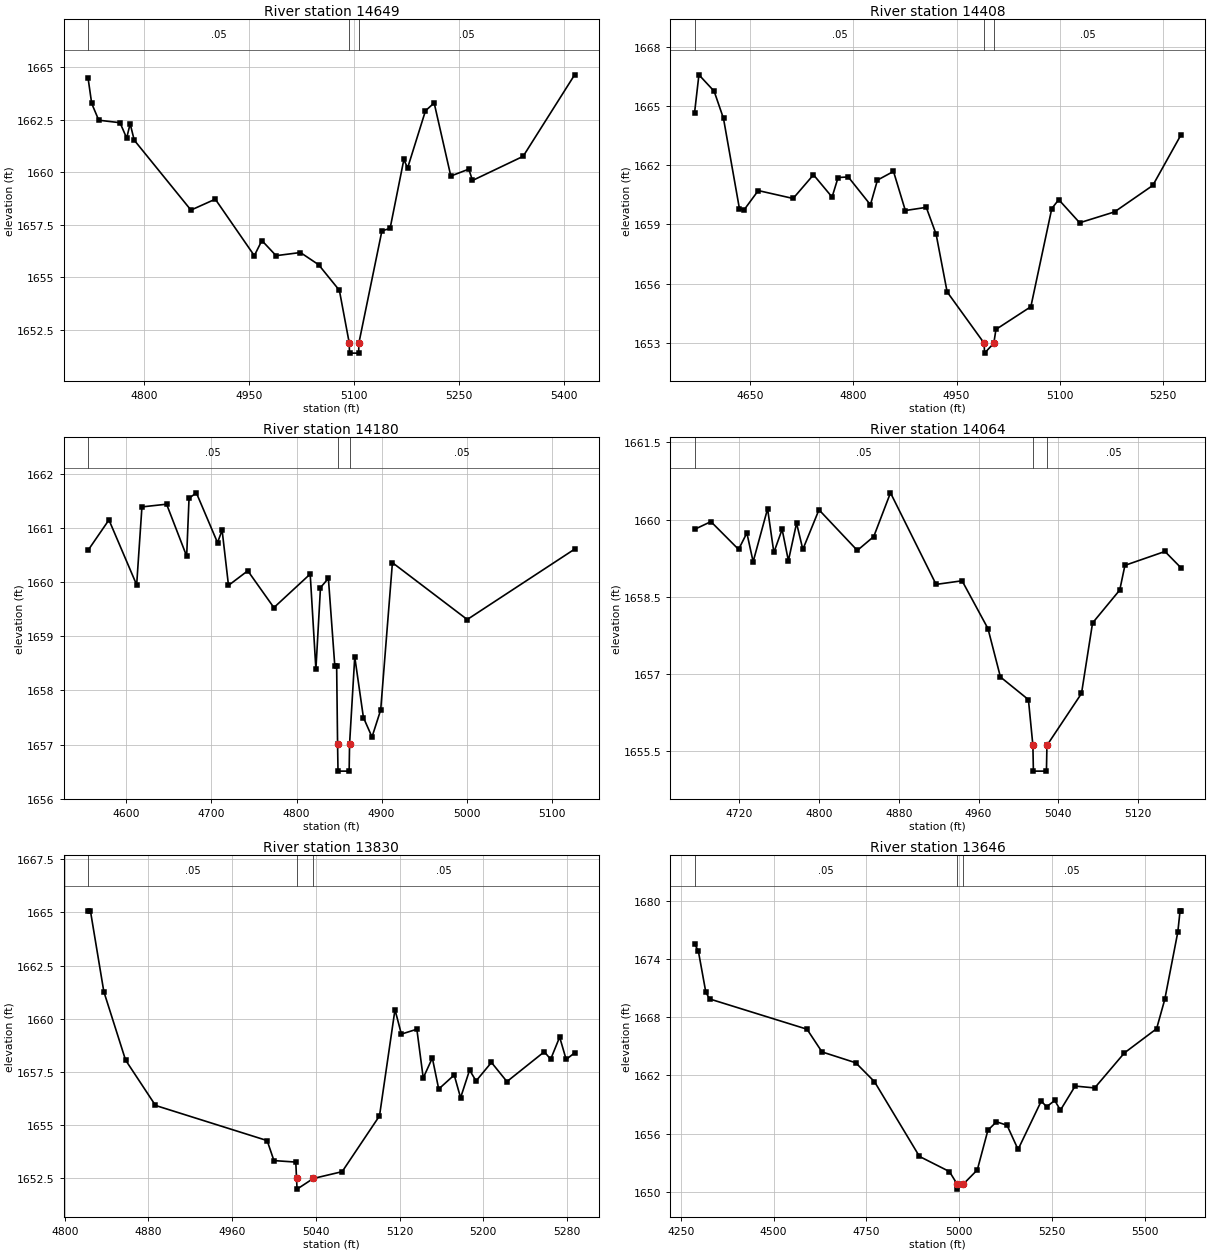
Type RM Length L Ch R = 1,14649,241,241,241
BEGIN DESCRIPTION:
Mapping XS 5fcc7caa
END DESCRIPTION:
XS GIS Cut Line= 3
      1593939.99      6926853.23      1594361.19      6926923.43
      1594614.37      6927012.79
#Sta/Elev= 30
  4719.5 1664.46  4724.6 1663.27  4734.7 1662.47  4765.1 1662.35  4774.6 1661.62
  4779.6 1662.30  4785.4 1661.52  4866.5 1658.19  4901.3 1658.71  4957.1 1656.02
  4967.9 1656.74  4988.2 1656.02  5023.0 1656.17  5049.0 1655.59  5078.7 1654.37
  5092.7 1651.88  5093.2 1651.38  5106.2 1651.38  5106.7 1651.88  5139.5 1657.20
  5151.2 1657.32  5170.9 1660.60  5176.2 1660.19  5201.8 1662.92  5214.2 1663.29
  5238.0 1659.81  5263.7 1660.14  5269.0 1659.60  5341.4 1660.75  5415.0 1664.63
#Mann=3,-1,0
  4719.5    0.05       0  5092.7    0.03       0  5106.7    0.05       0
Bank Sta=5092.7,5106.7
Exp/Cntr=0.3,0.1

Type RM Length L Ch R = 1,14408,228,228,228
BEGIN DESCRIPTION:
Mapping XS d05ac256
END DESCRIPTION:
XS GIS Cut Line= 3
      1593931.75      6927214.41      1594120.35      6927081.95
      1594590.46      6927006.47
#Sta/Elev= 30
  4569.5 1664.66  4575.8 1666.57  4597.9 1665.74  4611.5 1664.36  4634.6 1659.80
  4641.1 1659.72  4662.0 1660.71  4712.6 1660.31  4742.2 1661.51  4769.2 1660.38
  4777.9 1661.37  4792.7 1661.40  4824.9 1659.99  4835.1 1661.24  4858.4 1661.68
  4875.6 1659.70  4906.0 1659.86  4920.3 1658.50  4936.3 1655.58  4990.1 1652.98
  4990.6 1652.48  5004.1 1652.98  5007.2 1653.68  5057.9 1654.83  5088.3 1659.80
  5098.4 1660.25  5128.8 1659.08  5179.4 1659.63  5235.0 1660.97  5276.1 1663.54
#Mann=3,-1,0
  4569.5    0.05       0  4990.1    0.03       0  5004.1    0.05       0
Bank Sta=4990.1,5004.1
Exp/Cntr=0.3,0.1

Type RM Length L Ch R = 1,14180,116,116,116
BEGIN DESCRIPTION:
Mapping XS 1fa6b770
END DESCRIPTION:
XS GIS Cut Line= 4
      1594032.50      6927158.27      1594143.18      6927110.74
      1594304.12      6927171.09      1594579.10      6927223.16
#Sta/Elev= 30
  4554.9 1660.59  4579.4 1661.15  4612.0 1659.95  4618.2 1661.39  4647.2 1661.44
  4670.8 1660.48  4673.6 1661.55  4682.2 1661.65  4707.1 1660.73  4712.5 1660.96
  4720.0 1659.94  4742.7 1660.21  4773.4 1659.53  4816.1 1660.15  4822.8 1658.39
  4828.2 1659.90  4837.5 1660.07  4845.0 1658.46  4847.2 1658.46  4848.3 1657.01
  4848.8 1656.51  4861.9 1656.51  4862.4 1657.01  4868.5 1658.62  4878.7 1657.50
  4888.8 1657.14  4899.0 1657.64  4912.8 1660.36  5000.8 1659.31  5127.1 1660.61
#Mann=3,-1,0
  4554.9    0.05       0  4848.3    0.03       0  4862.4    0.05       0
Bank Sta=4848.3,4862.4
Exp/Cntr=0.3,0.1

Type RM Length L Ch R = 1,14064,234,234,234
BEGIN DESCRIPTION:
Mapping XS b0d1bc3e
END DESCRIPTION:
XS GIS Cut Line= 4
      1594141.94      6927178.41      1594237.80      6927251.05
      1594475.24      6927321.05      1594590.49      6927285.23
#Sta/Elev= 30
  4674.9 1659.81  4691.3 1659.96  4719.1 1659.42  4727.4 1659.74  4733.7 1659.18
  4748.2 1660.21  4754.5 1659.36  4762.8 1659.81  4769.1 1659.20  4777.3 1659.93
  4783.6 1659.42  4799.8 1660.19  4838.3 1659.40  4854.8 1659.67  4871.6 1660.52
  4917.4 1658.74  4943.5 1658.81  4969.5 1657.88  4982.0 1656.94  5010.1 1656.50
  5014.6 1655.61  5015.1 1655.11  5028.2 1655.11  5028.7 1655.61  5063.4 1656.62
  5074.5 1657.99  5101.8 1658.63  5107.0 1659.11  5147.2 1659.38  5163.4 1659.06
#Mann=3,-1,0
  4674.9    0.05       0  5014.6    0.03       0  5028.7    0.05       0
Bank Sta=5014.6,5028.7
Exp/Cntr=0.3,0.1

Type RM Length L Ch R = 1,13830,184,184,184
BEGIN DESCRIPTION:
Mapping XS 4be32dea
END DESCRIPTION:
XS GIS Cut Line= 3
      1594227.15      6927610.59      1594346.30      6927468.04
      1594573.93      6927306.36
#Sta/Elev= 30
  4822.3 1665.07  4824.5 1665.07  4837.3 1661.28  4858.1 1658.06  4886.7 1655.93
  4993.4 1654.28  4999.9 1653.34  5020.8 1653.27  5021.5 1652.50  5022.0 1652.00
  5037.5 1652.50  5065.1 1652.82  5100.8 1655.44  5115.6 1660.43  5121.7 1659.28
  5136.5 1659.51  5142.6 1657.22  5151.3 1658.16  5157.4 1656.70  5172.2 1657.36
  5178.3 1656.29  5186.9 1657.59  5193.1 1657.08  5207.8 1657.95  5222.6 1657.05
  5258.3 1658.45  5264.4 1658.10  5273.0 1659.14  5279.2 1658.09  5287.3 1658.40
#Mann=3,-1,0
  4822.3    0.05       0  5021.5    0.03       0  5037.5    0.05       0
Bank Sta=5021.5,5037.5
Exp/Cntr=0.3,0.1

Type RM Length L Ch R = 1,13646,464,464,464
BEGIN DESCRIPTION:
Deadman 07 28.0
END DESCRIPTION:
XS GIS Cut Line= 3
      1594405.00      6928238.00      1594505.00      6927538.00
      1594755.02      6926987.96
#Sta/Elev= 30
  4287.2 1675.55  4297.3 1674.84  4317.5 1670.58  4327.6 1669.89  4590.2 1666.77
  4630.6 1664.43  4721.6 1663.31  4772.1 1661.36  4893.3 1653.66  4974.1 1652.10
  4995.1 1650.79  4995.6 1650.29  5011.1 1650.79  5049.2 1652.27  5077.8 1656.36
  5100.9 1657.23  5129.4 1656.87  5159.1 1654.38  5221.7 1659.37  5236.0 1658.77
  5257.9 1659.43  5273.3 1658.43  5312.9 1660.91  5365.6 1660.72  5445.8 1664.33
  5532.5 1666.82  5554.5 1669.84  5589.7 1676.79  5595.7 1678.97  5598.5 1678.97
#Mann=3,-1,0
  4287.2    0.05       0  4995.1    0.03       0  5011.1    0.05       0
Bank Sta=4995.1,5011.1
Exp/Cntr=0.3,0.1

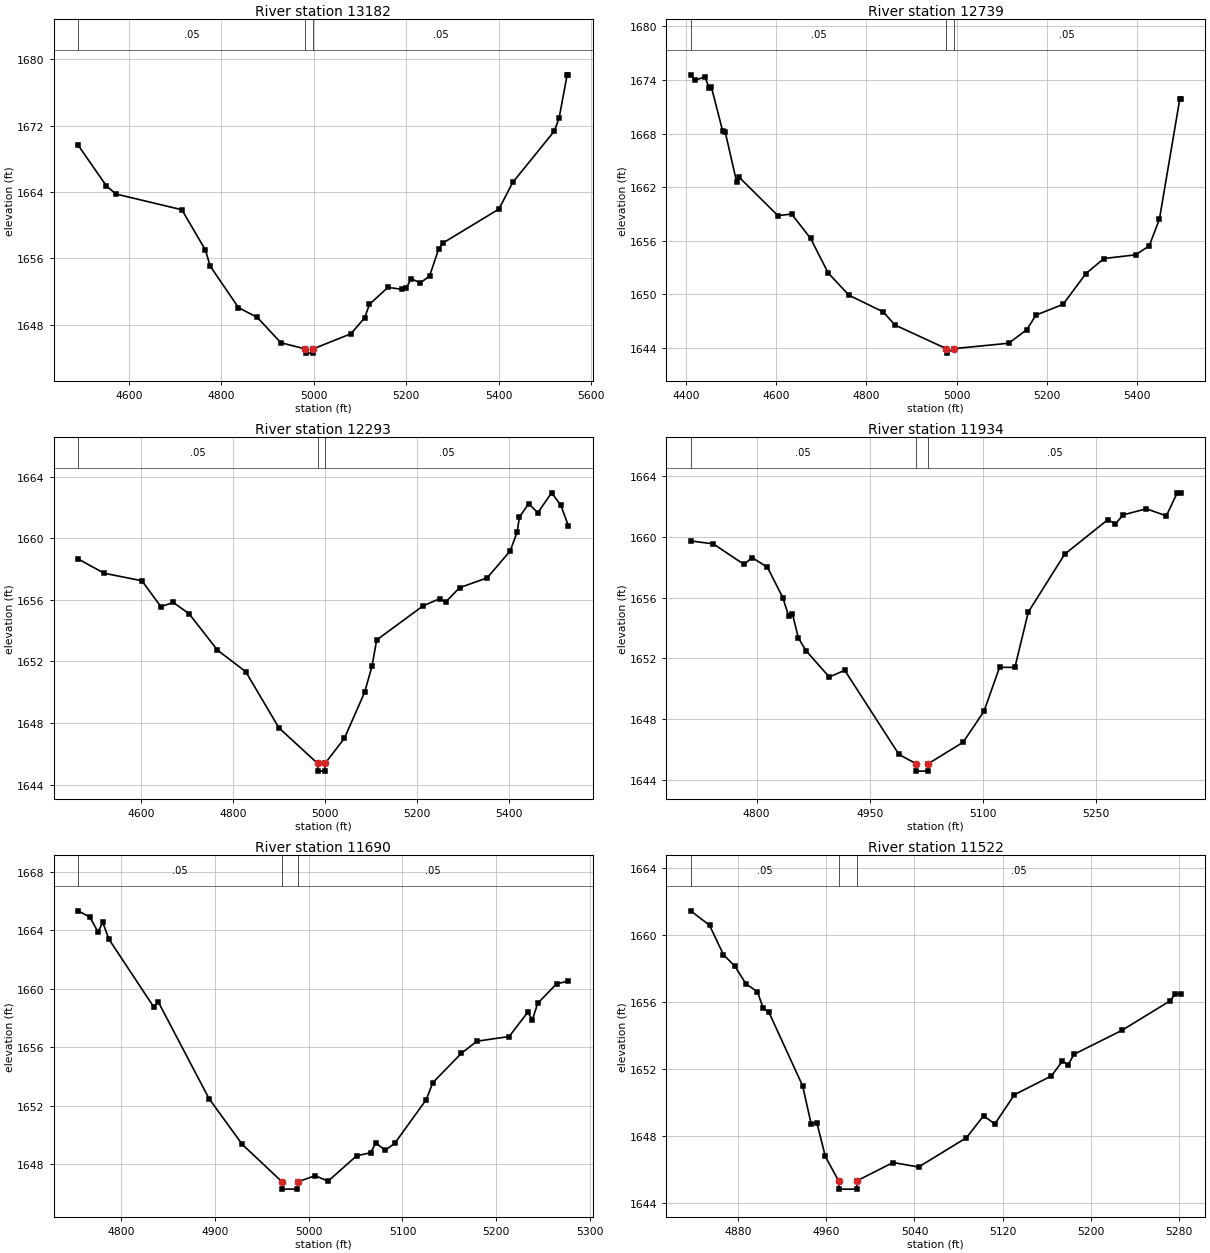
Type RM Length L Ch R = 1,13182,443,443,443
BEGIN DESCRIPTION:
Deadman 07 27.0
END DESCRIPTION:
XS GIS Cut Line= 3
      1594855.00      6928087.98      1594955.00      6927588.00
      1594955.00      6927037.98
#Sta/Elev= 30
  4490.3 1669.66  4551.5 1664.75  4571.9 1663.77  4714.6 1661.87  4765.6 1657.03
  4775.8 1655.10  4837.0 1650.09  4877.8 1648.90  4928.8 1645.85  4982.0 1645.10
  4982.5 1644.60  4997.5 1644.60  4998.0 1645.10  5080.2 1646.93  5110.2 1648.88
  5120.2 1650.47  5160.2 1652.52  5190.2 1652.29  5200.2 1652.44  5210.2 1653.56
  5230.2 1653.07  5250.2 1653.87  5270.2 1657.19  5280.2 1657.90  5400.2 1661.95
  5430.2 1665.17  5520.2 1671.36  5530.2 1672.89  5547.7 1678.12  5550.2 1678.12
#Mann=3,-1,0
  4490.3    0.05       0  4982.0    0.03       0  4998.0    0.05       0
Bank Sta=4982,4998
Exp/Cntr=0.3,0.1

Type RM Length L Ch R = 1,12739,446,446,446
BEGIN DESCRIPTION:
Deadman 07 26.0
END DESCRIPTION:
XS GIS Cut Line= 3
      1595155.00      6928188.01      1595355.00      6927638.00
      1595405.00      6927138.04
#Sta/Elev= 30
  4410.1 1674.58  4420.1 1673.97  4442.0 1674.36  4450.7 1673.13  4456.0 1673.23
  4481.3 1668.24  4486.6 1668.22  4511.9 1662.62  4517.2 1663.13  4603.6 1658.81
  4634.2 1658.98  4676.1 1656.26  4715.4 1652.37  4761.3 1649.89  4837.7 1648.01
  4863.0 1646.56  4977.3 1643.90  4977.8 1643.40  4993.4 1643.90  5115.9 1644.51
  5156.1 1646.04  5176.2 1647.66  5236.5 1648.87  5286.8 1652.30  5327.0 1654.00
  5397.3 1654.41  5427.5 1655.42  5450.1 1658.40  5495.3 1671.86  5497.8 1671.86
#Mann=3,-1,0
  4410.1    0.05       0  4977.3    0.05       0  4993.4    0.05       0
Bank Sta=4977.3,4993.4
Exp/Cntr=0.3,0.1

Type RM Length L Ch R = 1,12293,359,359,359
BEGIN DESCRIPTION:
Deadman 07 25.0
END DESCRIPTION:
XS GIS Cut Line= 3
      1595622.41      6928173.36      1595745.07      6927649.53
      1595713.32      6927121.79
#Sta/Elev= 30
  4462.0 1658.67  4518.9 1657.74  4601.0 1657.25  4642.1 1655.57  4669.3 1655.84
  4703.7 1655.10  4765.4 1652.74  4827.0 1651.33  4898.9 1647.69  4983.2 1645.37
  4983.7 1644.87  4999.0 1644.87  4999.5 1645.37  5041.6 1647.01  5085.6 1650.00
  5101.7 1651.71  5111.7 1653.40  5211.9 1655.60  5249.0 1656.09  5262.0 1655.87
  5292.1 1656.80  5352.2 1657.44  5402.3 1659.19  5417.4 1660.42  5422.4 1661.39
  5442.3 1662.26  5462.4 1661.68  5492.4 1662.97  5512.5 1662.16  5528.7 1660.84
#Mann=3,-1,0
  4462.0    0.05       0  4983.2    0.03       0  4999.5    0.05       0
Bank Sta=4983.2,4999.5
Exp/Cntr=0.3,0.1

Type RM Length L Ch R = 1,11934,244,244,244
BEGIN DESCRIPTION:
Mapping XS a8a0129c
END DESCRIPTION:
XS GIS Cut Line= 2
      1596010.85      6928017.16      1596154.09      6927383.45
#Sta/Elev= 30
  4712.6 1659.73  4742.5 1659.54  4783.5 1658.18  4793.8 1658.64  4814.3 1658.00
  4834.8 1655.99  4842.4 1654.79  4847.5 1654.93  4855.3 1653.34  4865.5 1652.50
  4896.3 1650.77  4916.8 1651.21  4988.6 1645.67  5010.9 1645.07  5011.4 1644.57
  5027.2 1644.57  5027.7 1645.07  5073.7 1646.47  5101.3 1648.51  5122.0 1651.41
  5142.3 1651.40  5160.0 1655.04  5208.3 1658.86  5265.4 1661.13  5275.6 1660.86
  5285.9 1661.45  5316.6 1661.85  5343.0 1661.38  5357.4 1662.90  5362.3 1662.90
#Mann=3,-1,0
  4712.6    0.05       0  5010.9    0.03       0  5027.7    0.05       0
Bank Sta=5010.9,5027.7
Exp/Cntr=0.3,0.1

Type RM Length L Ch R = 1,11690,168,168,168
BEGIN DESCRIPTION:
Mapping XS 52875f53
END DESCRIPTION:
XS GIS Cut Line= 2
      1596275.62      6927980.22      1596366.76      6927465.93
#Sta/Elev= 30
  4754.4 1665.33  4766.8 1664.91  4775.7 1663.89  4780.8 1664.54  4787.1 1663.41
  4834.8 1658.78  4839.9 1659.10  4893.9 1652.50  4929.3 1649.37  4971.7 1646.81
  4972.2 1646.31  4988.0 1646.31  4988.5 1646.81  5007.1 1647.23  5020.7 1646.85
  5051.2 1648.59  5066.2 1648.80  5071.5 1649.47  5081.6 1648.97  5091.8 1649.44
  5125.3 1652.42  5132.4 1653.59  5162.9 1655.60  5179.4 1656.42  5213.7 1656.74
  5233.4 1658.39  5238.5 1657.90  5244.1 1659.01  5264.4 1660.35  5276.7 1660.52
#Mann=3,-1,0
  4754.4    0.05       0  4971.7    0.03       0  4988.5    0.05       0
Bank Sta=4971.7,4988.5
Exp/Cntr=0.3,0.1

Type RM Length L Ch R = 1,11522,262,262,262
BEGIN DESCRIPTION:
Mapping XS 214f3703
END DESCRIPTION:
XS GIS Cut Line= 2
      1596435.68      6927947.04      1596532.25      6927513.46
#Sta/Elev= 30
  4837.2 1661.42  4854.3 1660.56  4866.9 1658.80  4877.2 1658.12  4887.4 1657.05
  4897.7 1656.59  4902.9 1655.61  4908.1 1655.36  4938.7 1650.96  4946.4 1648.69
  4951.6 1648.76  4959.2 1646.75  4971.2 1645.30  4971.7 1644.80  4987.5 1644.80
  4988.0 1645.30  5020.6 1646.39  5043.7 1646.12  5087.1 1647.87  5102.6 1649.18
  5112.8 1648.69  5130.6 1650.44  5164.1 1651.56  5174.1 1652.45  5179.2 1652.22
  5184.5 1652.85  5227.9 1654.28  5271.3 1656.03  5276.5 1656.47  5281.4 1656.47
#Mann=3,-1,0
  4837.2    0.05       0  4971.2    0.03       0  4988.0    0.05       0
Bank Sta=4971.2,4988
Exp/Cntr=0.3,0.1