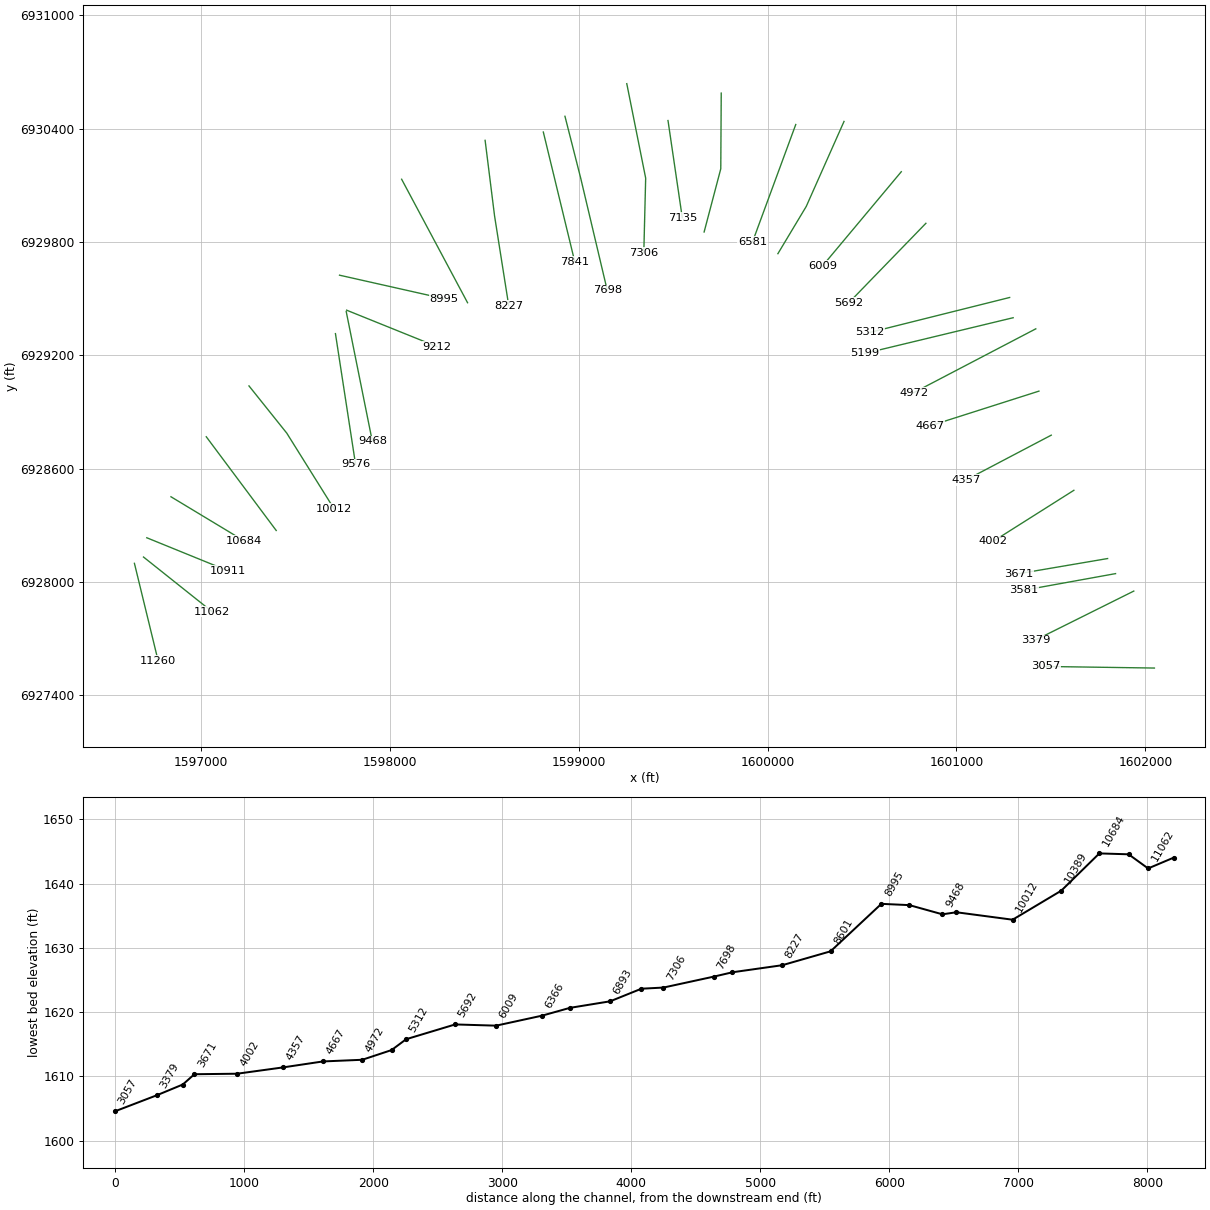
HEC-RAS study Deadman 07.prj: Deadman 07 Base Level Engineering

--- Deadman 07.g01 (geometry) --- (continued)

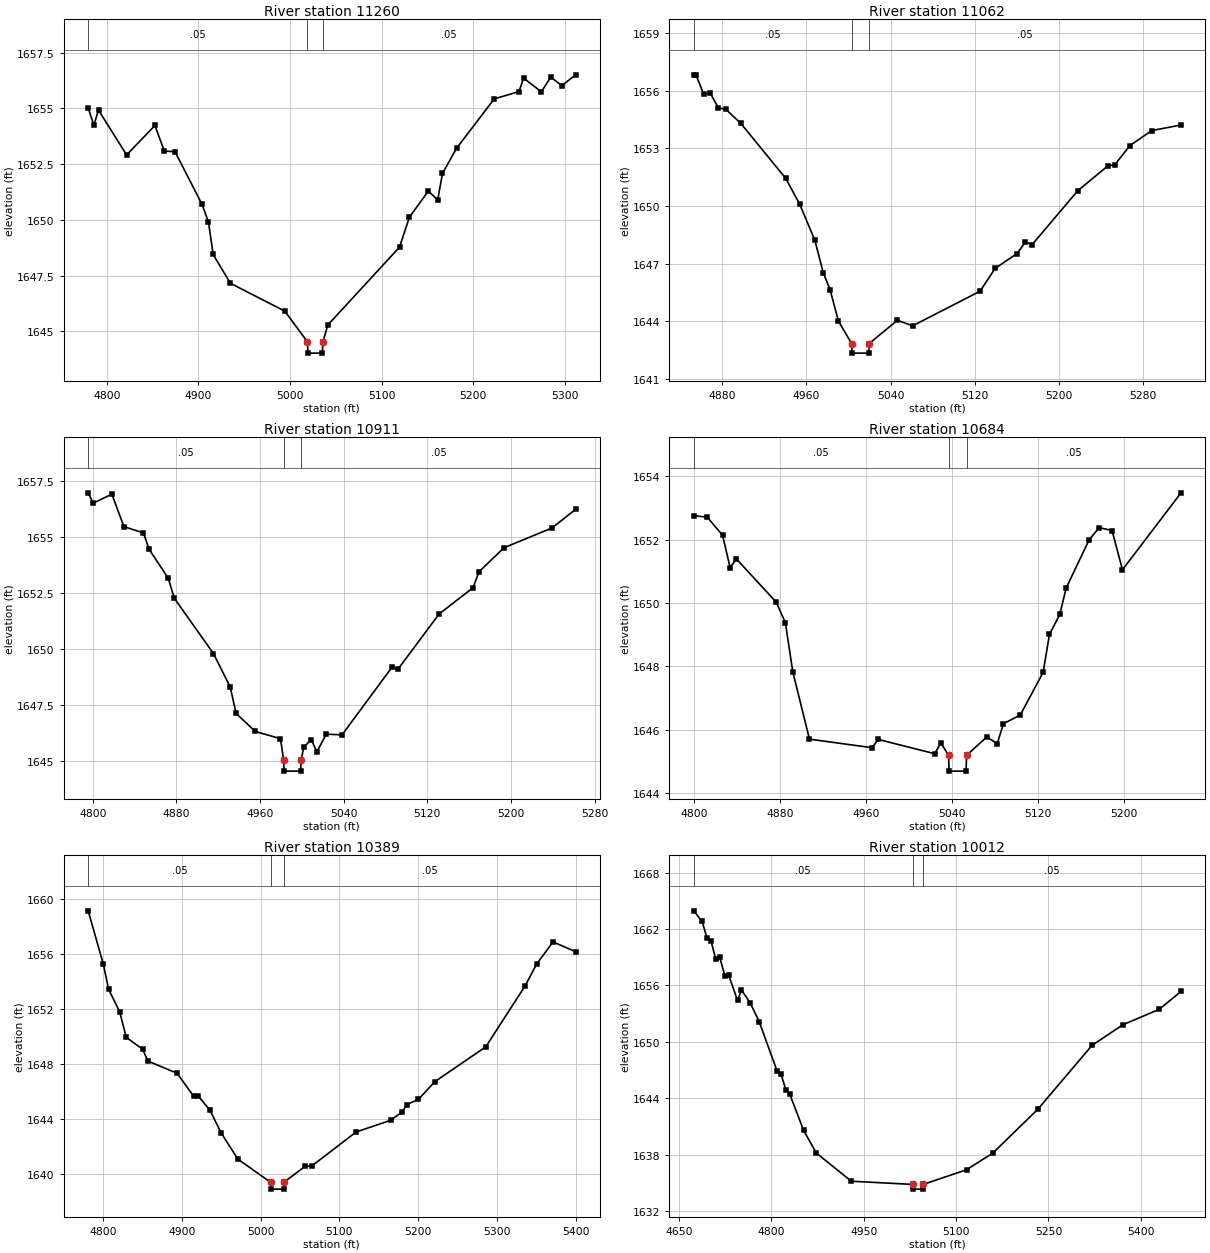
Type RM Length L Ch R = 1,11260,198,198,198
BEGIN DESCRIPTION:
Mapping XS 8e8f0a9d
END DESCRIPTION:
XS GIS Cut Line= 2
      1596648.50      6928098.85      1596774.34      6927581.74
#Sta/Elev= 30
  4779.6 1655.02  4785.8 1654.24  4790.9 1654.92  4821.6 1652.91  4852.5 1654.23
  4862.8 1653.08  4874.4 1653.06  4904.0 1650.69  4911.0 1649.90  4916.1 1648.45
  4934.9 1647.16  4994.4 1645.91  5019.1 1644.53  5019.6 1644.03  5035.4 1644.03
  5035.9 1644.53  5041.3 1645.29  5119.6 1648.78  5130.4 1650.12  5151.0 1651.29
  5161.3 1650.90  5166.5 1652.08  5181.9 1653.21  5223.0 1655.42  5250.0 1655.75
  5255.1 1656.35  5274.5 1655.74  5284.8 1656.40  5296.8 1656.01  5311.8 1656.50
#Mann=3,-1,0
  4779.6    0.05       0  5019.1    0.03       0  5035.9    0.05       0
Bank Sta=5019.1,5035.9
Exp/Cntr=0.3,0.1

Type RM Length L Ch R = 1,11062,151,151,151
BEGIN DESCRIPTION:
Mapping XS e53b81ba
END DESCRIPTION:
XS GIS Cut Line= 2
      1596696.61      6928132.16      1597059.02      6927843.53
#Sta/Elev= 30
  4852.8 1656.83  4855.0 1656.83  4862.3 1655.82  4868.7 1655.87  4876.3 1655.10
  4883.1 1655.05  4897.5 1654.31  4940.2 1651.45  4953.6 1650.10  4968.0 1648.22
  4976.0 1646.53  4982.4 1645.66  4990.4 1644.02  5002.9 1642.85  5003.4 1642.35
  5019.2 1642.35  5019.7 1642.85  5046.5 1644.06  5060.9 1643.77  5125.0 1645.57
  5139.4 1646.76  5160.2 1647.53  5168.2 1648.13  5174.6 1648.00  5217.9 1650.80
  5246.7 1652.10  5253.1 1652.15  5267.5 1653.15  5288.3 1653.93  5316.1 1654.22
#Mann=3,-1,0
  4852.8    0.05       0  5002.9    0.03       0  5019.7    0.05       0
Bank Sta=5002.9,5019.7
Exp/Cntr=0.3,0.1

Type RM Length L Ch R = 1,10911,227,227,227
BEGIN DESCRIPTION:
Mapping XS 7e2feaf3
END DESCRIPTION:
XS GIS Cut Line= 2
      1596713.98      6928234.14      1597145.87      6928058.35
#Sta/Elev= 30
  4795.5 1656.98  4800.3 1656.52  4818.2 1656.92  4829.7 1655.47  4848.4 1655.19
  4853.8 1654.46  4872.2 1653.16  4877.8 1652.28  4915.4 1649.80  4931.4 1648.31
  4937.0 1647.13  4955.4 1646.32  4979.5 1646.00  4982.5 1645.05  4983.0 1644.55
  4998.8 1644.55  4999.3 1645.05  5001.7 1645.61  5008.9 1645.96  5014.3 1645.41
  5023.3 1646.20  5038.4 1646.17  5086.5 1649.21  5091.9 1649.10  5131.3 1651.57
  5163.7 1652.74  5169.5 1653.46  5193.5 1654.53  5239.3 1655.41  5261.8 1656.24
#Mann=3,-1,0
  4795.5    0.05       0  4982.5    0.03       0  4999.3    0.05       0
Bank Sta=4982.5,4999.3
Exp/Cntr=0.3,0.1

Type RM Length L Ch R = 1,10684,295,295,295
BEGIN DESCRIPTION:
Mapping XS 35dd39de
END DESCRIPTION:
XS GIS Cut Line= 2
      1596841.99      6928451.17      1597230.20      6928216.95
#Sta/Elev= 30
  4799.7 1652.76  4812.3 1652.71  4826.6 1652.14  4833.6 1651.12  4839.5 1651.39
  4876.4 1650.03  4885.0 1649.38  4891.9 1647.83  4907.4 1645.70  4965.6 1645.43
  4971.5 1645.69  5023.9 1645.24  5029.7 1645.58  5036.8 1645.19  5037.3 1644.69
  5053.1 1644.69  5053.6 1645.19  5072.4 1645.77  5082.1 1645.56  5087.9 1646.19
  5103.5 1646.46  5124.8 1647.81  5130.7 1649.01  5140.3 1649.64  5146.2 1650.47
  5167.5 1651.99  5176.9 1652.38  5188.9 1652.29  5198.6 1651.05  5253.1 1653.48
#Mann=3,-1,0
  4799.7    0.05       0  5036.8    0.03       0  5053.6    0.05       0
Bank Sta=5036.8,5053.6
Exp/Cntr=0.3,0.1

Type RM Length L Ch R = 1,10389,377,377,377
BEGIN DESCRIPTION:
Mapping XS c8509627
END DESCRIPTION:
XS GIS Cut Line= 2
      1597028.86      6928768.85      1597399.06      6928272.63
#Sta/Elev= 30
  4780.9 1659.12  4800.1 1655.26  4806.9 1653.41  4820.9 1651.79  4829.3 1649.92
  4850.1 1649.06  4856.8 1648.20  4893.9 1647.31  4914.8 1645.65  4921.0 1645.64
  4935.6 1644.62  4950.2 1642.94  4971.1 1641.07  5012.6 1639.39  5013.1 1638.89
  5029.1 1638.89  5029.6 1639.39  5056.5 1640.55  5064.9 1640.57  5121.2 1643.04
  5165.0 1643.89  5179.6 1644.49  5185.8 1645.04  5200.4 1645.41  5221.2 1646.70
  5285.9 1649.23  5335.9 1653.66  5350.5 1655.24  5371.4 1656.86  5400.0 1656.15
#Mann=3,-1,0
  4780.9    0.05       0  5012.6    0.05       0  5029.6    0.05       0
Bank Sta=5012.6,5029.6
Exp/Cntr=0.3,0.1

Type RM Length L Ch R = 1,10012,436,436,436
BEGIN DESCRIPTION:
Deadman 07 20.0
END DESCRIPTION:
XS GIS Cut Line= 3
      1597254.98      6929038.02      1597455.00      6928788.00
      1597705.01      6928387.98
#Sta/Elev= 30
  4673.6 1663.93  4687.2 1662.82  4695.2 1661.06  4701.6 1660.76  4709.6 1658.78
  4716.0 1658.98  4724.1 1657.06  4730.5 1657.10  4744.9 1654.41  4751.3 1655.52
  4765.7 1654.12  4780.1 1652.15  4808.9 1646.95  4815.3 1646.63  4823.3 1644.93
  4829.7 1644.46  4852.1 1640.63  4872.9 1638.20  4929.8 1635.21  5029.5 1634.87
  5030.0 1634.37  5046.0 1634.37  5046.5 1634.87  5117.0 1636.43  5159.5 1638.19
  5232.6 1642.84  5321.0 1649.65  5371.1 1651.83  5430.1 1653.47  5465.5 1655.37
#Mann=3,-1,0
  4673.6    0.05       0  5029.5    0.03       0  5046.5    0.05       0
Bank Sta=5029.5,5046.5
Exp/Cntr=0.3,0.1

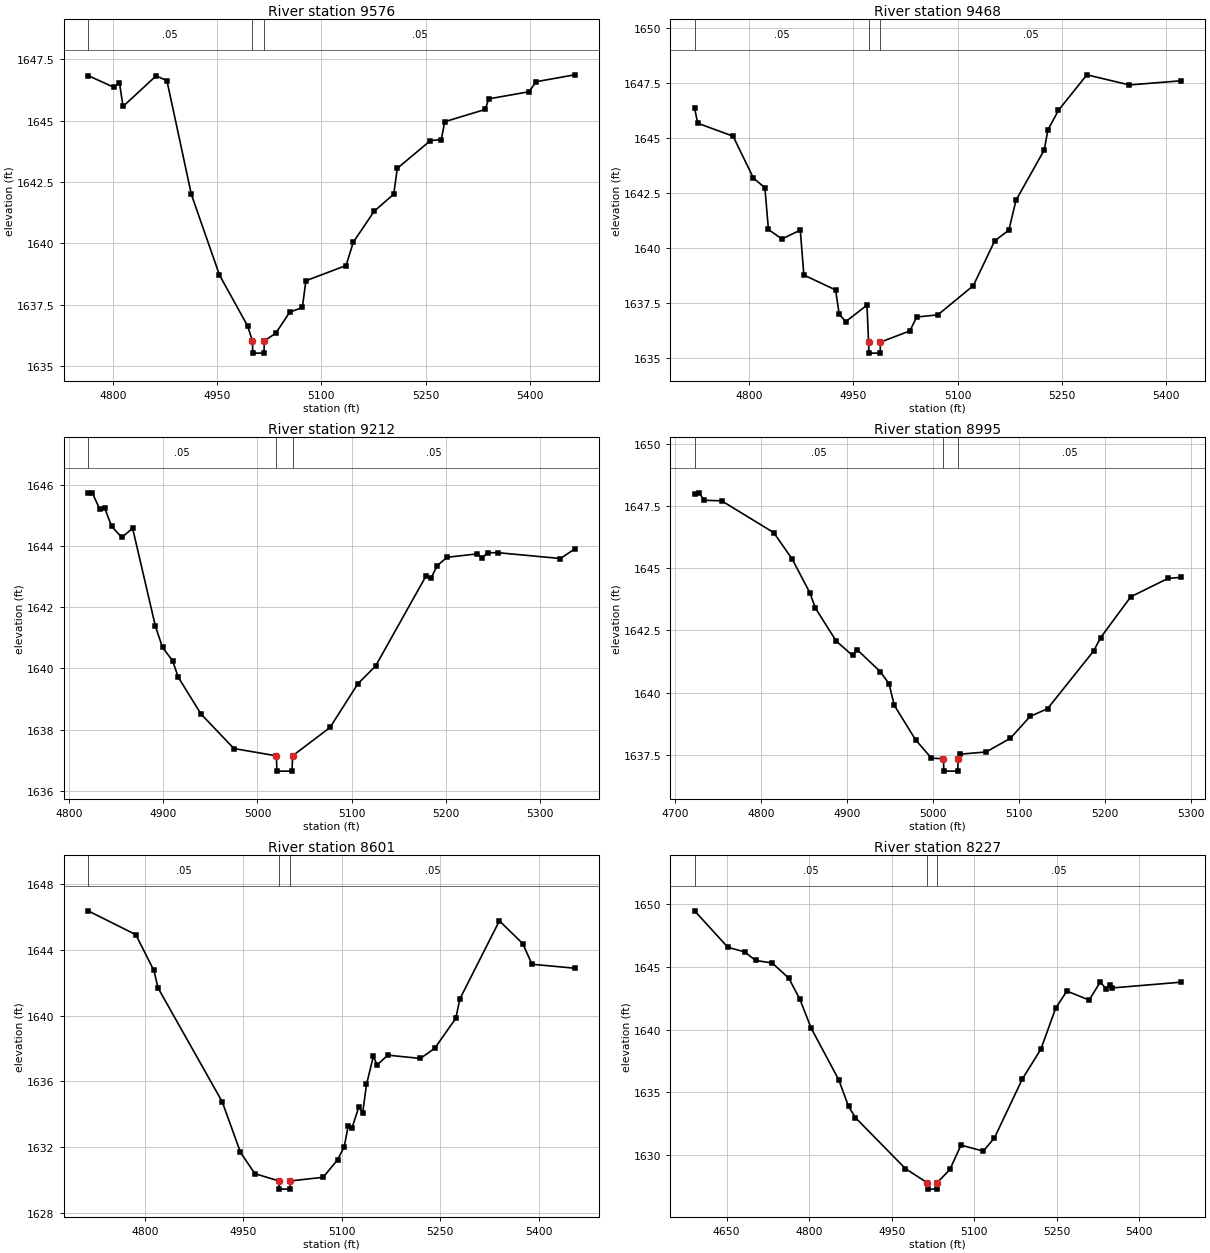
Type RM Length L Ch R = 1,9576,108,108,108
BEGIN DESCRIPTION:
Mapping XS 83a0010a
END DESCRIPTION:
XS GIS Cut Line= 2
      1597712.70      6929314.76      1597819.12      6928623.00
#Sta/Elev= 30
  4764.5 1646.84  4801.7 1646.36  4809.6 1646.55  4814.7 1645.58  4862.4 1646.83
  4877.9 1646.63  4913.0 1642.00  4953.5 1638.71  4993.9 1636.64  5000.9 1636.03
  5001.4 1635.53  5017.5 1635.53  5018.0 1636.03  5034.4 1636.34  5054.6 1637.20
  5072.7 1637.39  5077.8 1638.48  5135.6 1639.10  5146.0 1640.05  5176.0 1641.31
  5204.2 1642.01  5209.3 1643.06  5257.0 1644.19  5272.5 1644.23  5277.6 1644.96
  5335.8 1645.46  5340.8 1645.89  5398.6 1646.18  5409.1 1646.59  5464.4 1646.87
#Mann=3,-1,0
  4764.5    0.05       0  5000.9   0.035       0  5018.0    0.05       0
Bank Sta=5000.9,5018
Exp/Cntr=0.3,0.1

Type RM Length L Ch R = 1,9468,256,256,256
BEGIN DESCRIPTION:
Mapping XS d4cd02cd
END DESCRIPTION:
XS GIS Cut Line= 2
      1597769.84      6929431.06      1597907.80      6928745.20
#Sta/Elev= 30
  4721.8 1646.34  4726.3 1645.66  4777.2 1645.07  4806.5 1643.16  4822.9 1642.73
  4828.0 1640.83  4847.3 1640.40  4873.8 1640.80  4878.9 1638.76  4924.6 1638.08
  4929.7 1636.99  4939.1 1636.64  4969.7 1637.39  4972.0 1635.71  4972.5 1635.21
  4988.6 1635.21  4989.1 1635.71  5031.4 1636.22  5041.1 1636.85  5071.7 1636.95
  5122.7 1638.28  5153.3 1640.31  5173.7 1640.80  5184.0 1642.16  5224.7 1644.45
  5229.8 1645.35  5245.1 1646.25  5285.9 1647.86  5347.1 1647.40  5421.4 1647.59
#Mann=3,-1,0
  4721.8    0.05       0  4972.0   0.035       0  4989.1    0.05       0
Bank Sta=4972,4989.1
Exp/Cntr=0.3,0.1

Type RM Length L Ch R = 1,9212,217,217,217
BEGIN DESCRIPTION:
Mapping XS 925b71c1
END DESCRIPTION:
XS GIS Cut Line= 2
      1597771.84      6929438.89      1598250.39      6929245.89
#Sta/Elev= 30
  4820.4 1645.75  4824.8 1645.75  4832.7 1645.22  4838.1 1645.24  4845.4 1644.65
  4856.2 1644.29  4867.6 1644.59  4891.8 1641.38  4899.3 1640.69  4910.1 1640.25
  4915.9 1639.72  4940.1 1638.51  4975.0 1637.38  5020.1 1637.14  5020.6 1636.64
  5036.7 1636.64  5037.2 1637.14  5077.0 1638.07  5106.5 1639.50  5125.3 1640.08
  5179.0 1643.04  5184.4 1642.97  5190.4 1643.36  5201.2 1643.64  5232.7 1643.75
  5238.1 1643.62  5244.3 1643.79  5255.1 1643.79  5321.3 1643.60  5336.4 1643.91
#Mann=3,-1,0
  4820.4    0.05       0  5020.1   0.035       0  5037.2    0.05       0
Bank Sta=5020.1,5037.2
Exp/Cntr=0.3,0.1

Type RM Length L Ch R = 1,8995,394,394,394
BEGIN DESCRIPTION:
Mapping XS eb09630c
END DESCRIPTION:
XS GIS Cut Line= 2
      1597734.41      6929624.14      1598286.21      6929499.98
#Sta/Elev= 30
  4722.6 1647.97  4728.1 1648.03  4733.5 1647.73  4754.0 1647.71  4814.6 1646.43
  4836.0 1645.37  4856.5 1644.02  4863.0 1643.40  4887.2 1642.07  4906.3 1641.49
  4911.4 1641.73  4938.5 1640.84  4948.7 1640.35  4954.7 1639.49  4979.5 1638.10
  4998.0 1637.36  5011.9 1637.34  5012.4 1636.84  5028.5 1636.84  5029.0 1637.34
  5030.7 1637.52  5061.5 1637.61  5089.7 1638.16  5112.7 1639.04  5132.9 1639.35
  5186.5 1641.67  5194.7 1642.21  5229.7 1643.85  5273.0 1644.59  5288.2 1644.63
#Mann=3,-1,0
  4722.6    0.05       0  5011.9   0.035       0  5029.0    0.05       0
Bank Sta=5011.9,5029
Exp/Cntr=0.3,0.1

Type RM Length L Ch R = 1,8601,374,374,374
BEGIN DESCRIPTION:
Mapping XS 93f3292b
END DESCRIPTION:
XS GIS Cut Line= 2
      1598063.13      6930132.05      1598412.10      6929478.37
#Sta/Elev= 30
  4713.6 1646.38  4786.2 1644.93  4813.8 1642.75  4820.2 1641.68  4917.9 1634.76
  4945.6 1631.69  4967.6 1630.39  5004.1 1629.95  5004.6 1629.45  5021.2 1629.45
  5021.7 1629.95  5071.6 1630.17  5093.6 1631.24  5103.6 1632.02  5109.8 1633.30
  5115.5 1633.17  5126.1 1634.47  5131.8 1634.09  5137.6 1635.82  5148.1 1637.53
  5153.7 1637.00  5170.0 1637.60  5219.6 1637.40  5241.6 1638.02  5273.6 1639.84
  5279.8 1641.02  5340.0 1645.77  5375.7 1644.38  5389.6 1643.13  5454.6 1642.89
#Mann=3,-1,0
  4713.6    0.05       0  5004.1   0.035       0  5021.7    0.05       0
Bank Sta=5004.1,5021.7
Exp/Cntr=0.3,0.1

Type RM Length L Ch R = 1,8227,386,386,386
BEGIN DESCRIPTION:
Deadman 07 17.0
END DESCRIPTION:
XS GIS Cut Line= 3
      1598505.00      6930338.02      1598555.00      6929938.00
      1598630.00      6929463.02
#Sta/Elev= 30
  4591.7 1649.49  4652.2 1646.58  4682.4 1646.22  4702.6 1645.53  4732.8 1645.33
  4763.0 1644.11  4783.2 1642.42  4803.4 1640.14  4853.7 1636.01  4871.4 1633.89
  4884.0 1632.99  4974.7 1628.93  5014.7 1627.79  5015.2 1627.29  5031.8 1627.29
  5032.3 1627.79  5055.6 1628.86  5075.8 1630.80  5116.3 1630.32  5136.6 1631.38
  5187.2 1636.07  5220.9 1638.45  5247.9 1641.73  5268.2 1643.09  5308.7 1642.37
  5328.9 1643.82  5339.0 1643.28  5345.8 1643.61  5350.9 1643.34  5475.7 1643.80
#Mann=3,-1,0
  4591.7    0.05       0  5014.7    0.05       0  5032.3    0.05       0
Bank Sta=5014.7,5032.3
Exp/Cntr=0.3,0.1

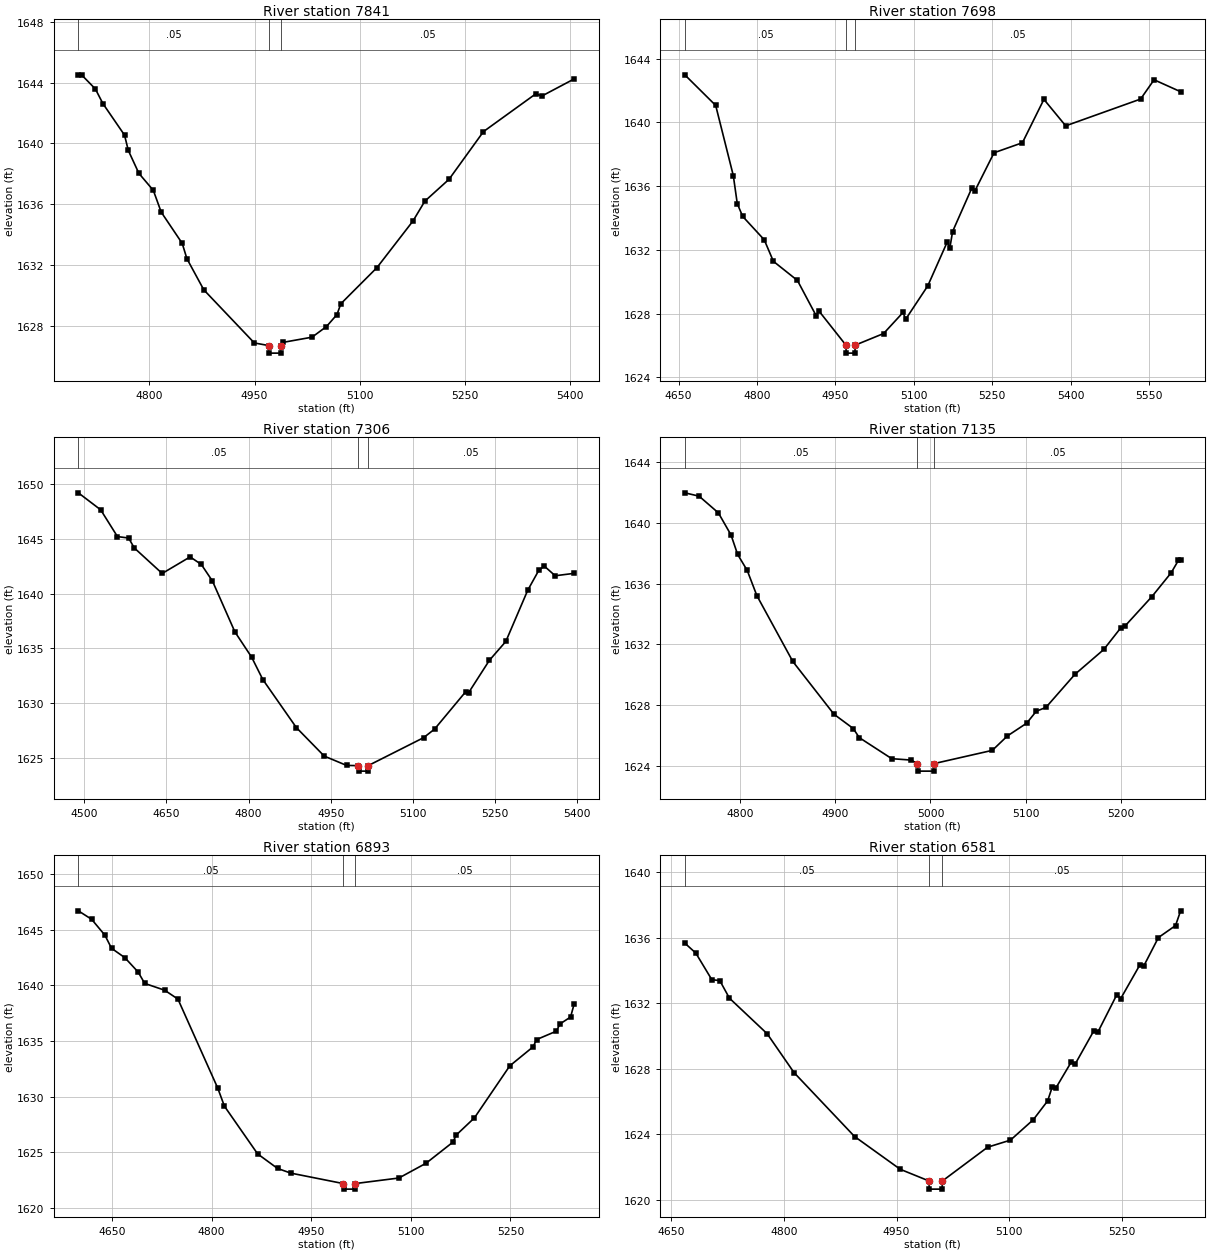
Type RM Length L Ch R = 1,7841,143,143,143
BEGIN DESCRIPTION:
Mapping XS 3e4c73f7
END DESCRIPTION:
XS GIS Cut Line= 2
      1598813.14      6930382.00      1598979.81      6929694.51
#Sta/Elev= 30
  4698.6 1644.52  4703.2 1644.52  4722.9 1643.59  4733.6 1642.63  4764.5 1640.55
  4769.9 1639.54  4785.0 1638.03  4805.6 1636.91  4816.8 1635.48  4846.8 1633.42
  4853.5 1632.41  4877.6 1630.36  4949.7 1626.86  4970.0 1626.69  4970.5 1626.19
  4987.2 1626.19  4987.7 1626.69  4990.8 1626.90  5032.0 1627.24  5052.6 1627.94
  5067.6 1628.73  5073.1 1629.44  5124.6 1631.82  5176.0 1634.89  5193.0 1636.20
  5227.5 1637.64  5276.6 1640.78  5351.0 1643.26  5360.2 1643.13  5406.0 1644.25
#Mann=3,-1,0
  4698.6    0.05       0  4970.0   0.035       0  4987.7    0.05       0
Bank Sta=4970,4987.7
Exp/Cntr=0.3,0.1

Type RM Length L Ch R = 1,7698,392,392,392
BEGIN DESCRIPTION:
Deadman 07 16.0
END DESCRIPTION:
XS GIS Cut Line= 3
      1598927.73      6930465.32      1599011.14      6930137.46
      1599151.68      6929543.46
#Sta/Elev= 30
  4661.7 1642.98  4720.8 1641.06  4754.5 1636.66  4762.1 1634.90  4772.4 1634.10
  4813.7 1632.63  4831.2 1631.28  4877.2 1630.08  4913.0 1627.87  4918.2 1628.17
  4970.0 1626.02  4970.5 1625.52  4987.2 1625.52  4987.7 1626.02  5042.1 1626.75
  5079.2 1628.07  5084.4 1627.65  5126.6 1629.74  5163.8 1632.49  5168.9 1632.13
  5174.1 1633.15  5211.2 1635.90  5216.3 1635.67  5253.4 1638.09  5307.7 1638.72
  5348.8 1641.44  5390.5 1639.78  5533.8 1641.46  5559.6 1642.67  5610.4 1641.92
#Mann=3,-1,0
  4661.7    0.05       0  4970.0    0.05       0  4987.7    0.05       0
Bank Sta=4970,4987.7
Exp/Cntr=0.3,0.1

Type RM Length L Ch R = 1,7306,171,171,171
BEGIN DESCRIPTION:
Deadman 07 15.0
END DESCRIPTION:
XS GIS Cut Line= 3
      1599254.99      6930638.03      1599355.00      6930138.00
      1599345.09      6929743.36
#Sta/Elev= 30
  4489.5 1649.18  4530.3 1647.63  4560.9 1645.19  4581.3 1645.06  4591.5 1644.16
  4642.5 1641.83  4693.5 1643.34  4713.9 1642.65  4734.3 1641.13  4775.1 1636.51
  4805.7 1634.20  4826.1 1632.16  4887.3 1627.78  4938.2 1625.18  4979.0 1624.33
  5000.5 1624.31  5001.0 1623.81  5017.8 1623.81  5018.3 1624.31  5119.5 1626.86
  5139.5 1627.64  5196.5 1631.06  5201.5 1630.95  5239.5 1633.91  5269.5 1635.63
  5309.5 1640.30  5329.5 1642.10  5339.5 1642.51  5359.6 1641.62  5394.2 1641.84
#Mann=3,-1,0
  4489.5    0.05       0  5000.5   0.035       0  5018.3    0.05       0
Bank Sta=5000.5,5018.3
Exp/Cntr=0.3,0.1

Type RM Length L Ch R = 1,7135,242,242,242
BEGIN DESCRIPTION:
Mapping XS 2396aa42
END DESCRIPTION:
XS GIS Cut Line= 2
      1599473.20      6930442.81      1599548.82      6929928.24
#Sta/Elev= 30
  4742.3 1641.98  4757.3 1641.76  4777.5 1640.66  4790.8 1639.20  4797.7 1637.92
  4807.8 1636.86  4817.9 1635.20  4855.6 1630.86  4898.8 1627.38  4919.0 1626.44
  4925.3 1625.84  4959.4 1624.45  4979.6 1624.36  4986.2 1624.13  4986.7 1623.63
  5003.5 1623.63  5004.0 1624.13  5064.9 1625.00  5080.7 1625.95  5100.9 1626.79
  5111.0 1627.58  5121.1 1627.83  5151.5 1630.01  5181.8 1631.65  5199.4 1633.06
  5204.4 1633.22  5232.3 1635.14  5252.5 1636.71  5260.0 1637.52  5262.4 1637.52
#Mann=3,-1,0
  4742.3    0.05       0  4986.2   0.035       0  5004.0    0.05       0
Bank Sta=4986.2,5004
Exp/Cntr=0.3,0.1

Type RM Length L Ch R = 1,6893,312,312,312
BEGIN DESCRIPTION:
Deadman 07 14.0
END DESCRIPTION:
XS GIS Cut Line= 3
      1599755.00      6930588.04      1599752.58      6930187.35
      1599664.37      6929852.78
#Sta/Elev= 30
  4599.3 1646.70  4619.3 1645.94  4639.3 1644.51  4649.3 1643.33  4669.3 1642.49
  4689.3 1641.20  4699.3 1640.17  4729.3 1639.56  4749.3 1638.76  4809.3 1630.75
  4819.3 1629.13  4869.3 1624.84  4899.3 1623.53  4919.3 1623.11  4998.3 1622.17
  4998.8 1621.67  5015.8 1621.67  5016.3 1622.17  5082.1 1622.67  5123.0 1624.00
  5163.3 1625.89  5168.5 1626.54  5195.8 1628.08  5249.1 1632.76  5284.2 1634.47
  5289.4 1635.12  5319.3 1635.88  5324.5 1636.52  5340.6 1637.15  5346.0 1638.33
#Mann=3,-1,0
  4599.3    0.05       0  4998.3   0.035       0  5016.3    0.05       0
Bank Sta=4998.3,5016.3
Exp/Cntr=0.3,0.1

Type RM Length L Ch R = 1,6581,215,215,215
BEGIN DESCRIPTION:
Mapping XS 45caf6ed
END DESCRIPTION:
XS GIS Cut Line= 2
      1600149.49      6930421.78      1599921.11      6929801.60
#Sta/Elev= 30
  4667.8 1635.66  4682.5 1635.05  4703.8 1633.43  4714.5 1633.37  4727.3 1632.30
  4777.6 1630.13  4813.4 1627.76  4894.1 1623.86  4955.0 1621.86  4993.2 1621.15
  4993.7 1620.65  5010.7 1620.65  5011.2 1621.15  5071.5 1623.21  5101.9 1623.64
  5132.4 1624.89  5151.4 1626.03  5157.5 1626.87  5162.8 1626.85  5182.6 1628.38
  5187.9 1628.26  5213.1 1630.32  5218.4 1630.23  5243.5 1632.50  5248.9 1632.28
  5274.0 1634.30  5279.3 1634.24  5299.1 1636.00  5321.9 1636.73  5328.7 1637.63
#Mann=3,-1,0
  4667.8    0.05       0  4993.2   0.035       0  5011.2    0.05       0
Bank Sta=4993.2,5011.2
Exp/Cntr=0.3,0.1

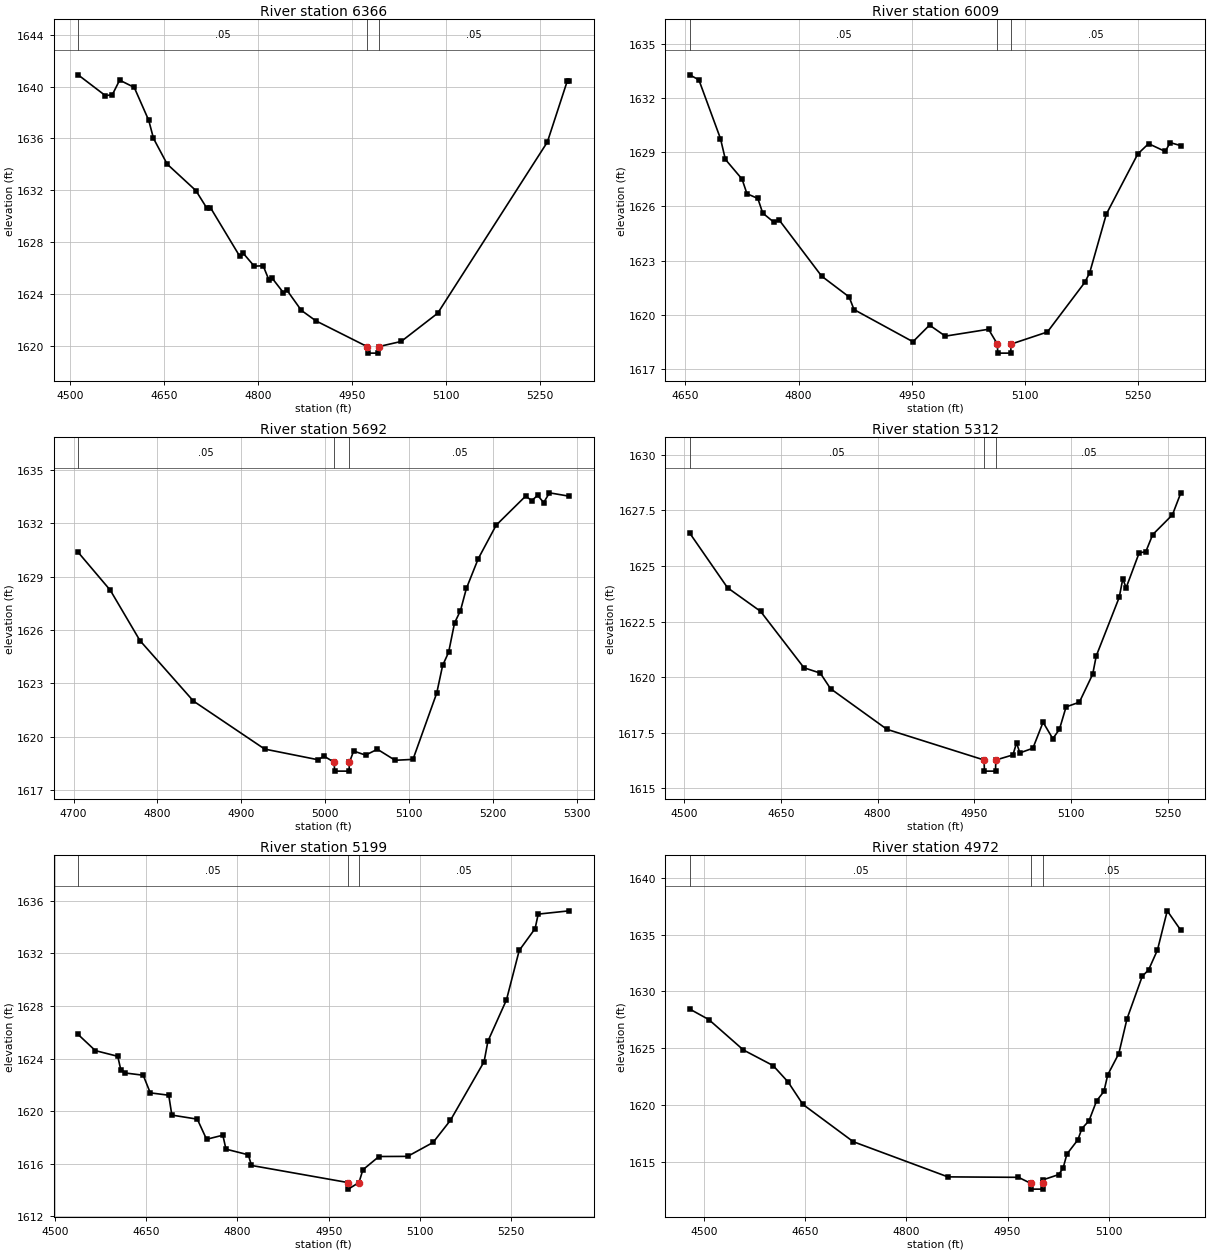
Type RM Length L Ch R = 1,6366,357,357,357
BEGIN DESCRIPTION:
Deadman 07 13.0
END DESCRIPTION:
XS GIS Cut Line= 3
      1600404.98      6930437.96      1600205.00      6929988.00
      1600054.97      6929737.96
#Sta/Elev= 30
  4512.4 1640.91  4556.1 1639.30  4567.1 1639.38  4578.7 1640.50  4602.0 1639.94
  4625.2 1637.39  4632.7 1636.01  4654.6 1634.02  4700.4 1631.98  4718.2 1630.60
  4723.7 1630.66  4770.2 1626.93  4775.7 1627.16  4793.5 1626.15  4807.8 1626.18
  4816.7 1625.12  4822.2 1625.22  4840.0 1624.11  4845.4 1624.32  4868.7 1622.74
  4892.0 1621.93  4973.9 1619.94  4974.4 1619.44  4991.4 1619.44  4991.9 1619.94
  5028.1 1620.34  5086.4 1622.52  5261.4 1635.72  5293.4 1640.46  5296.4 1640.46
#Mann=3,-1,0
  4512.4    0.05       0  4973.9   0.035       0  4991.9    0.05       0
Bank Sta=4973.9,4991.9
Exp/Cntr=0.3,0.1

Type RM Length L Ch R = 1,6009,317,317,317
BEGIN DESCRIPTION:
Mapping XS 822033bc
END DESCRIPTION:
XS GIS Cut Line= 2
      1600708.19      6930171.89      1600290.61      6929672.47
#Sta/Elev= 30
  4655.6 1633.28  4667.8 1633.00  4696.4 1629.75  4702.9 1628.60  4725.0 1627.51
  4731.5 1626.70  4745.9 1626.44  4752.4 1625.63  4766.7 1625.14  4774.5 1625.23
  4830.5 1622.14  4866.9 1620.99  4873.4 1620.29  4951.5 1618.51  4973.5 1619.43
  4994.4 1618.82  5051.7 1619.20  5063.4 1618.38  5063.9 1617.88  5081.1 1617.88
  5081.6 1618.38  5129.7 1619.05  5179.2 1621.79  5185.7 1622.32  5207.8 1625.57
  5249.5 1628.90  5263.8 1629.47  5285.9 1629.04  5292.4 1629.53  5306.6 1629.36
#Mann=3,-1,0
  4655.6    0.05       0  5063.4   0.035       0  5081.6    0.05       0
Bank Sta=5063.4,5081.6
Exp/Cntr=0.3,0.1

Type RM Length L Ch R = 1,5692,380,380,380
BEGIN DESCRIPTION:
Mapping XS 36787580
END DESCRIPTION:
XS GIS Cut Line= 2
      1600838.40      6929898.85      1600430.95      6929478.79
#Sta/Elev= 30
  4705.4 1630.38  4743.8 1628.24  4779.1 1625.41  4842.8 1622.01  4927.7 1619.31
  4991.3 1618.71  4998.4 1618.91  5010.5 1618.57  5011.0 1618.07  5028.2 1618.07
  5028.7 1618.57  5033.7 1619.20  5047.9 1618.97  5062.0 1619.30  5083.1 1618.68
  5104.4 1618.73  5132.7 1622.46  5139.7 1624.01  5146.9 1624.76  5153.9 1626.40
  5161.0 1627.10  5168.0 1628.34  5182.1 1630.01  5203.5 1631.90  5238.7 1633.54
  5245.9 1633.28  5252.9 1633.58  5260.1 1633.17  5267.0 1633.72  5290.6 1633.53
#Mann=3,-1,0
  4705.4    0.05       0  5010.5   0.035       0  5028.7    0.05       0
Bank Sta=5010.5,5028.7
Exp/Cntr=0.3,0.1

Type RM Length L Ch R = 1,5312,113,113,113
BEGIN DESCRIPTION:
Mapping XS 8edcc564
END DESCRIPTION:
XS GIS Cut Line= 2
      1601281.59      6929506.09      1600542.24      6929321.25
#Sta/Elev= 30
  4508.4 1626.48  4567.1 1624.02  4618.3 1622.96  4685.7 1620.42  4711.0 1620.18
  4726.9 1619.48  4814.5 1617.65  4965.2 1616.27  4965.7 1615.77  4982.9 1615.77
  4983.4 1616.27  5010.0 1616.50  5015.5 1617.04  5020.7 1616.59  5040.9 1616.80
  5056.7 1617.97  5071.8 1617.23  5082.1 1617.65  5092.4 1618.66  5113.0 1618.87
  5133.7 1620.13  5139.2 1620.95  5174.9 1623.59  5180.4 1624.42  5185.6 1624.02
  5205.8 1625.59  5216.1 1625.64  5226.8 1626.41  5257.4 1627.30  5270.5 1628.29
#Mann=3,-1,0
  4508.4    0.05       0  4965.2    0.05       0  4983.4    0.05       0
Bank Sta=4965.2,4983.4
Exp/Cntr=0.3,0.1

Type RM Length L Ch R = 1,5199,227,227,227
BEGIN DESCRIPTION:
Mapping XS 4eee1632
END DESCRIPTION:
XS GIS Cut Line= 2
      1601300.42      6929398.96      1600514.95      6929209.94
#Sta/Elev= 30
  4537.9 1625.84  4566.3 1624.61  4603.1 1624.18  4608.2 1623.14  4615.5 1622.91
  4645.0 1622.74  4656.6 1621.40  4687.0 1621.22  4692.1 1619.71  4734.0 1619.40
  4749.2 1617.87  4776.0 1618.18  4781.1 1617.12  4817.9 1616.69  4823.1 1615.88
  4981.7 1614.58  4982.2 1614.08  4999.9 1614.58  5006.3 1615.55  5032.8 1616.56
  5079.9 1616.57  5121.8 1617.63  5150.3 1619.31  5205.7 1623.77  5212.0 1625.33
  5242.5 1628.47  5263.5 1632.23  5289.6 1633.89  5294.7 1634.99  5345.8 1635.24
#Mann=3,-1,0
  4537.9    0.05       0  4981.7    0.05       0  4999.9    0.05       0
Bank Sta=4981.7,4999.9
Exp/Cntr=0.3,0.1

Type RM Length L Ch R = 1,4972,305,305,305
BEGIN DESCRIPTION:
Mapping XS 831cc3c4
END DESCRIPTION:
XS GIS Cut Line= 2
      1601420.20      6929340.18      1600774.23      6929002.51
#Sta/Elev= 30
  4478.3 1628.45  4506.7 1627.52  4558.0 1624.84  4602.2 1623.46  4624.3 1622.02
  4646.3 1620.04  4721.1 1616.75  4861.5 1613.65  4966.2 1613.61  4984.8 1613.07
  4985.3 1612.57  5002.5 1612.57  5003.0 1613.07  5003.2 1613.40  5025.8 1613.85
  5032.4 1614.41  5038.1 1615.66  5054.5 1616.93  5060.2 1617.90  5070.9 1618.60
  5082.2 1620.36  5093.0 1621.18  5098.7 1622.65  5115.1 1624.52  5127.3 1627.59
  5149.9 1631.34  5159.3 1631.90  5172.5 1633.66  5187.0 1637.11  5207.2 1635.39
#Mann=3,-1,0
  4478.3    0.05       0  4984.8    0.05       0  5003.0    0.05       0
Bank Sta=4984.8,5003
Exp/Cntr=0.3,0.1

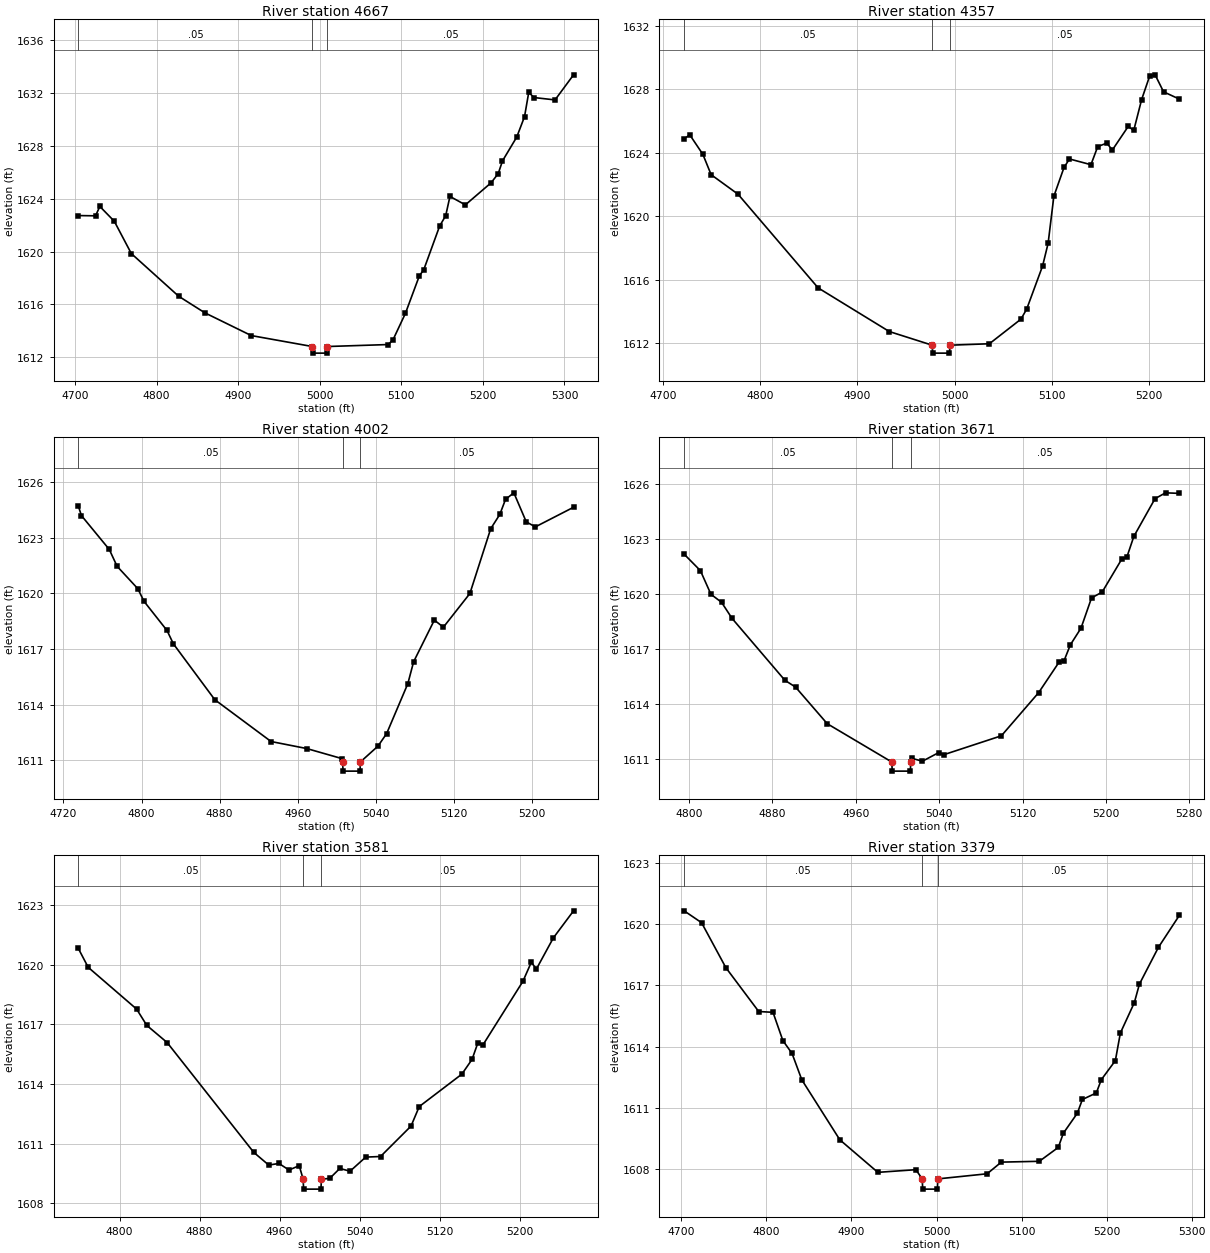
Type RM Length L Ch R = 1,4667,310,310,310
BEGIN DESCRIPTION:
Mapping XS b5b7aa59
END DESCRIPTION:
XS GIS Cut Line= 2
      1601436.98      6929010.41      1600858.66      6928826.02
#Sta/Elev= 30
  4704.1 1622.73  4725.2 1622.71  4730.5 1623.42  4748.2 1622.30  4769.1 1619.85
  4827.1 1616.62  4859.3 1615.36  4916.1 1613.64  4991.0 1612.81  4991.5 1612.31
  5008.7 1612.31  5009.2 1612.81  5084.0 1612.96  5089.9 1613.33  5105.0 1615.32
  5122.2 1618.18  5127.4 1618.61  5147.0 1621.94  5154.4 1622.72  5159.6 1624.18
  5178.5 1623.54  5210.0 1625.21  5218.8 1625.91  5224.0 1626.87  5241.5 1628.68
  5251.0 1630.22  5256.2 1632.07  5262.5 1631.67  5288.4 1631.49  5311.1 1633.39
#Mann=3,-1,0
  4704.1    0.05       0  4991.0    0.05       0  5009.2    0.05       0
Bank Sta=4991,5009.2
Exp/Cntr=0.3,0.1

Type RM Length L Ch R = 1,4357,355,355,355
BEGIN DESCRIPTION:
Mapping XS df0f17e4
END DESCRIPTION:
XS GIS Cut Line= 2
      1601502.07      6928777.28      1601050.54      6928539.96
#Sta/Elev= 30
  4721.5 1624.88  4727.3 1625.13  4740.8 1623.90  4749.3 1622.62  4777.0 1621.39
  4859.5 1615.49  4932.8 1612.74  4977.0 1611.88  4977.5 1611.38  4994.8 1611.38
  4995.3 1611.88  5035.9 1611.97  5068.4 1613.52  5074.3 1614.15  5090.7 1616.87
  5096.4 1618.30  5102.3 1621.26  5112.8 1623.08  5118.4 1623.61  5140.5 1623.25
  5147.5 1624.39  5156.9 1624.61  5162.5 1624.17  5178.9 1625.66  5184.6 1625.41
  5192.7 1627.35  5200.9 1628.82  5206.6 1628.91  5215.3 1627.84  5231.6 1627.38
#Mann=3,-1,0
  4721.5    0.05       0  4977.0    0.05       0  4995.3    0.05       0
Bank Sta=4977,4995.3
Exp/Cntr=0.3,0.1

Type RM Length L Ch R = 1,4002,331,331,331
BEGIN DESCRIPTION:
Mapping XS efc4cb75
END DESCRIPTION:
XS GIS Cut Line= 2
      1601621.76      6928485.32      1601193.33      6928214.41
#Sta/Elev= 30
  4735.3 1624.73  4738.5 1624.21  4767.0 1622.38  4775.0 1621.47  4796.2 1620.26
  4802.5 1619.58  4826.1 1618.00  4832.6 1617.28  4875.0 1614.26  4932.6 1612.00
  4969.1 1611.62  5005.6 1611.07  5005.8 1610.90  5006.3 1610.40  5023.6 1610.40
  5024.1 1610.90  5042.0 1611.75  5050.9 1612.43  5072.6 1615.13  5078.5 1616.31
  5099.7 1618.56  5109.0 1618.18  5136.1 1620.00  5157.4 1623.50  5166.7 1624.27
  5172.6 1625.09  5181.1 1625.44  5193.8 1623.87  5203.1 1623.60  5242.2 1624.66
#Mann=3,-1,0
  4735.3    0.05       0  5005.8    0.05       0  5024.1    0.05       0
Bank Sta=5005.8,5024.1
Exp/Cntr=0.3,0.1

Type RM Length L Ch R = 1,3671,90,90,90
BEGIN DESCRIPTION:
Mapping XS 8adba511
END DESCRIPTION:
XS GIS Cut Line= 2
      1601800.35      6928124.10      1601331.91      6928044.28
#Sta/Elev= 30
  4795.3 1622.17  4810.9 1621.27  4821.0 1619.98  4831.2 1619.54  4841.3 1618.66
  4892.0 1615.28  4902.2 1614.91  4932.6 1612.91  4994.5 1610.82  4995.0 1610.32
  5012.3 1610.32  5012.8 1610.82  5013.8 1611.02  5023.9 1610.86  5039.5 1611.33
  5044.6 1611.22  5099.7 1612.25  5135.5 1614.61  5154.9 1616.26  5159.9 1616.36
  5165.9 1617.22  5176.1 1618.13  5186.2 1619.78  5196.4 1620.10  5215.1 1621.89
  5220.1 1622.01  5226.8 1623.14  5247.1 1625.20  5257.2 1625.52  5270.5 1625.49
#Mann=3,-1,0
  4795.3    0.05       0  4994.5    0.05       0  5012.8    0.05       0
Bank Sta=4994.5,5012.8
Exp/Cntr=0.3,0.1

Type RM Length L Ch R = 1,3581,202,202,202
BEGIN DESCRIPTION:
Mapping XS 19f33596
END DESCRIPTION:
XS GIS Cut Line= 2
      1601842.36      6928044.29      1601355.09      6927956.08
#Sta/Elev= 30
  4758.8 1620.82  4768.7 1619.87  4817.1 1617.77  4827.3 1616.95  4847.6 1616.09
  4934.2 1610.57  4949.2 1609.93  4959.4 1610.01  4969.5 1609.68  4979.7 1609.90
  4983.6 1609.22  4984.1 1608.72  5001.4 1608.72  5001.9 1609.22  5010.2 1609.26
  5020.3 1609.76  5030.5 1609.62  5046.2 1610.33  5061.0 1610.36  5091.5 1611.89
  5099.7 1612.87  5142.3 1614.50  5152.5 1615.24  5158.3 1616.07  5163.4 1615.97
  5203.3 1619.16  5211.8 1620.13  5216.8 1619.78  5233.8 1621.35  5254.0 1622.71
#Mann=3,-1,0
  4758.8    0.05       0  4983.6    0.05       0  5001.9    0.05       0
Bank Sta=4983.6,5001.9
Exp/Cntr=0.3,0.1

Type RM Length L Ch R = 1,3379,322,322,322
BEGIN DESCRIPTION:
Mapping XS 58a6f2b5
END DESCRIPTION:
XS GIS Cut Line= 2
      1601938.91      6927951.86      1601417.57      6927692.24
#Sta/Elev= 30
  4703.2 1620.64  4723.7 1620.06  4752.3 1617.86  4790.9 1615.72  4807.7 1615.68
  4819.3 1614.30  4830.1 1613.67  4841.6 1612.38  4886.3 1609.45  4931.0 1607.86
  4975.7 1607.99  4983.2 1607.54  4983.7 1607.04  5001.0 1607.04  5001.5 1607.54
  5059.5 1607.79  5076.2 1608.36  5120.9 1608.40  5143.2 1609.08  5149.1 1609.77
  5165.6 1610.75  5171.5 1611.42  5187.9 1611.74  5193.8 1612.39  5210.3 1613.32
  5216.2 1614.67  5232.6 1616.15  5238.6 1617.06  5261.0 1618.86  5285.6 1620.42
#Mann=3,-1,0
  4703.2    0.05       0  4983.2    0.05       0  5001.5    0.05       0
Bank Sta=4983.2,5001.5
Exp/Cntr=0.3,0.1

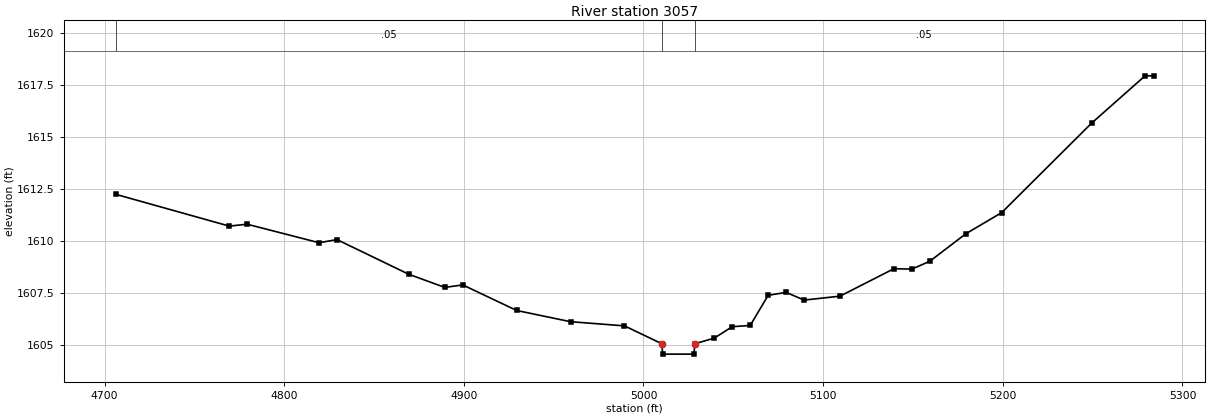
Type RM Length L Ch R = 1,3057,243,243,243
BEGIN DESCRIPTION:
Mapping XS 93340769
END DESCRIPTION:
XS GIS Cut Line= 2
      1602048.18      6927544.42      1601470.54      6927552.82
#Sta/Elev= 30
  4706.2 1612.25  4769.4 1610.72  4779.4 1610.81  4819.4 1609.92  4829.4 1610.07
  4869.4 1608.40  4889.4 1607.77  4899.4 1607.89  4929.4 1606.66  4959.4 1606.12
  4989.4 1605.92  5010.2 1605.06  5010.7 1604.56  5028.1 1604.56  5028.6 1605.06
  5039.4 1605.33  5049.4 1605.88  5059.4 1605.94  5069.4 1607.39  5079.4 1607.53
  5089.4 1607.16  5109.4 1607.35  5139.4 1608.67  5149.4 1608.65  5159.4 1609.03
  5179.4 1610.35  5199.4 1611.37  5249.4 1615.67  5279.2 1617.95  5283.9 1617.95
#Mann=3,-1,0
  4706.2    0.05       0  5010.2    0.03       0  5028.6    0.05       0
Bank Sta=5010.2,5028.6
Exp/Cntr=0.3,0.1