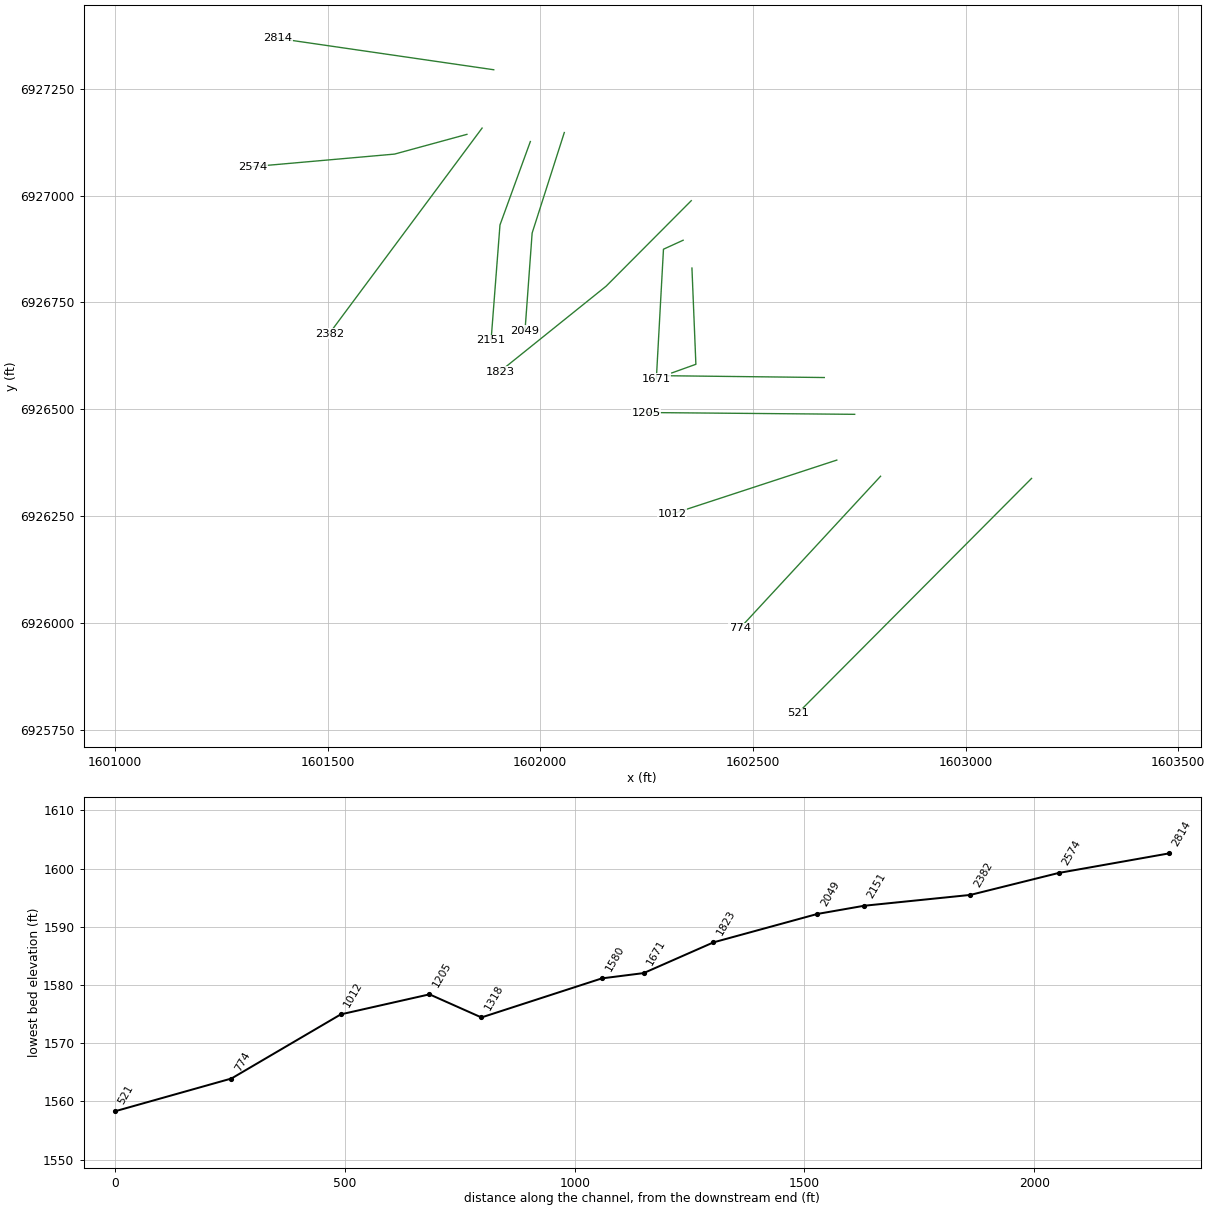
HEC-RAS study Deadman 07.prj: Deadman 07 Base Level Engineering

--- Deadman 07.g01 (geometry) --- (continued)

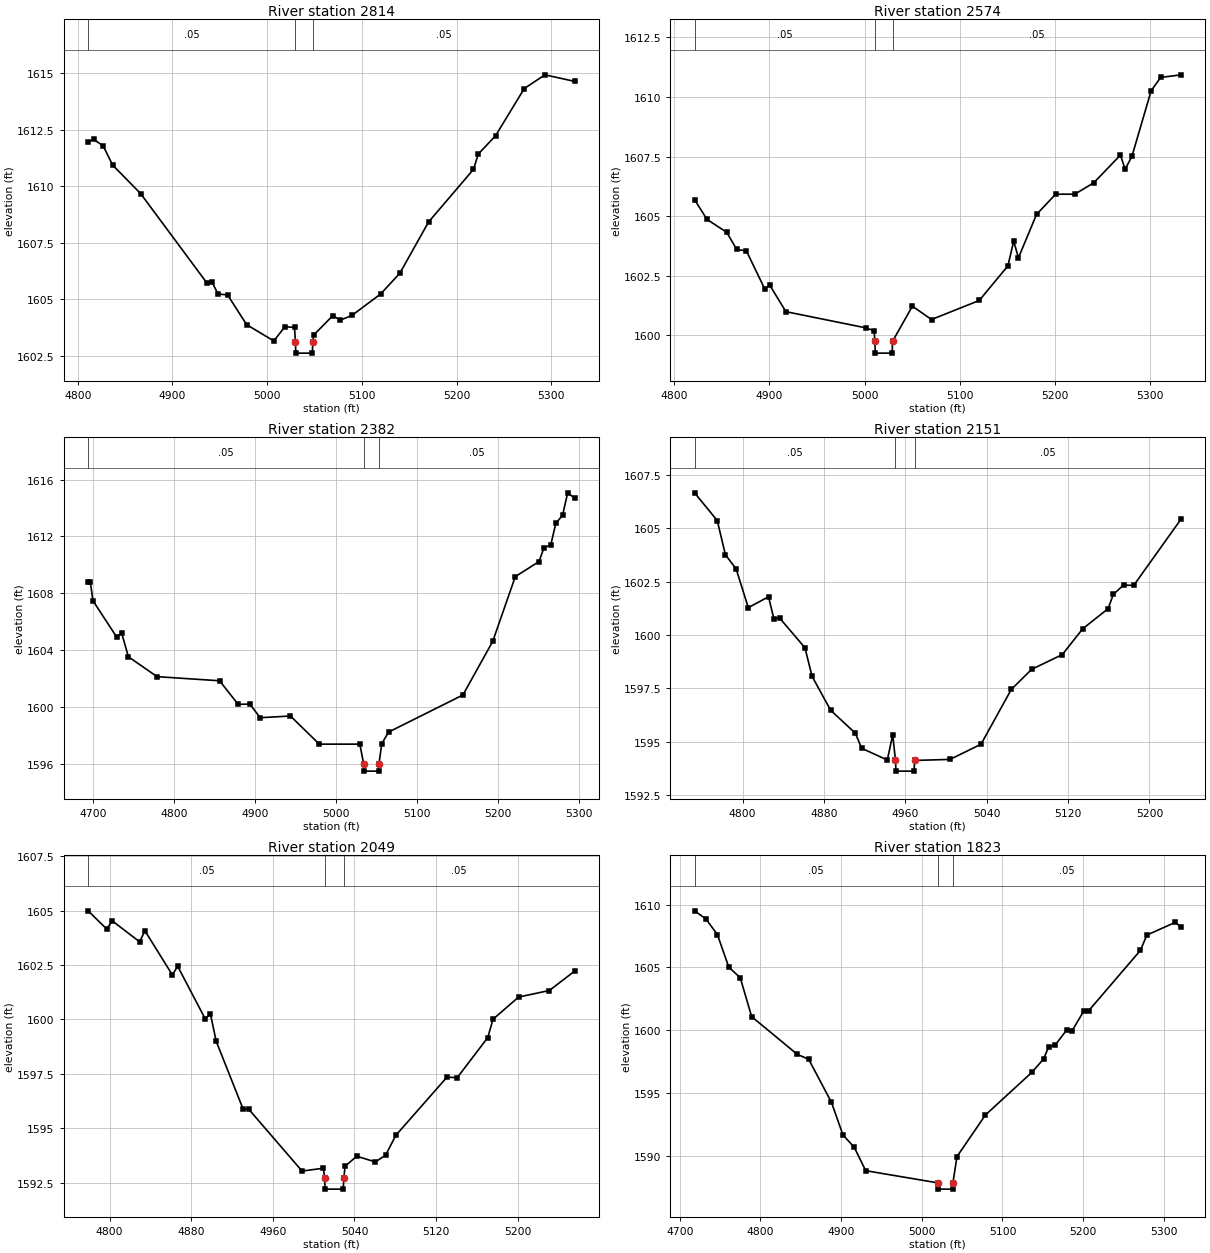
Type RM Length L Ch R = 1,2814,240,240,240
BEGIN DESCRIPTION:
Mapping XS 524e77be
END DESCRIPTION:
XS GIS Cut Line= 2
      1601890.67      6927294.48      1601382.36      6927368.00
#Sta/Elev= 30
  4811.0 1611.97  4816.7 1612.08  4826.8 1611.80  4836.9 1610.94  4866.4 1609.68
  4936.7 1605.70  4941.7 1605.77  4948.1 1605.23  4958.2 1605.19  4978.4 1603.87
  5007.0 1603.15  5018.8 1603.78  5028.9 1603.75  5029.8 1603.11  5030.3 1602.61
  5047.7 1602.61  5048.2 1603.11  5049.1 1603.41  5069.3 1604.27  5077.2 1604.07
  5089.5 1604.28  5119.8 1605.23  5140.1 1606.15  5170.4 1608.42  5217.8 1610.75
  5222.9 1611.43  5241.1 1612.24  5271.4 1614.33  5293.2 1614.94  5324.6 1614.65
#Mann=3,-1,0
  4811.0    0.05       0  5029.8    0.03       0  5048.2    0.05       0
Bank Sta=5029.8,5048.2
Exp/Cntr=0.3,0.1

Type RM Length L Ch R = 1,2574,192,192,192
BEGIN DESCRIPTION:
Mapping XS f21f0b17
END DESCRIPTION:
XS GIS Cut Line= 3
      1601827.63      6927143.27      1601657.49      6927097.06
      1601323.59      6927067.66
#Sta/Elev= 30
  4821.3 1605.69  4834.4 1604.86  4855.1 1604.32  4865.6 1603.60  4875.8 1603.54
  4895.0 1601.95  4900.2 1602.11  4917.3 1600.99  5001.4 1600.31  5010.1 1600.19
  5010.8 1599.75  5011.3 1599.25  5029.0 1599.25  5029.5 1599.75  5050.3 1601.22
  5070.4 1600.66  5120.6 1601.46  5150.7 1602.91  5156.8 1603.95  5161.8 1603.25
  5180.8 1605.07  5200.9 1605.92  5221.0 1605.92  5241.0 1606.40  5269.0 1607.56
  5274.0 1606.97  5281.2 1607.52  5301.3 1610.26  5311.3 1610.82  5332.8 1610.93
#Mann=3,-1,0
  4821.3    0.05       0  5010.8    0.05       0  5029.5    0.05       0
Bank Sta=5010.8,5029.5
Exp/Cntr=0.3,0.1

Type RM Length L Ch R = 1,2382,231,231,231
BEGIN DESCRIPTION:
Mapping XS 7446d0e1
END DESCRIPTION:
XS GIS Cut Line= 2
      1601863.31      6927157.96      1601504.20      6926677.04
#Sta/Elev= 30
  4694.1 1608.77  4696.9 1608.77  4700.0 1607.48  4729.2 1604.93  4735.4 1605.21
  4743.8 1603.53  4779.2 1602.13  4856.3 1601.84  4879.2 1600.18  4893.7 1600.20
  4906.3 1599.24  4943.7 1599.36  4979.3 1597.38  5029.3 1597.38  5034.1 1595.98
  5034.6 1595.48  5052.4 1595.48  5052.9 1595.98  5056.4 1597.42  5064.8 1598.23
  5156.5 1600.84  5193.3 1604.62  5221.1 1609.17  5250.3 1610.23  5256.5 1611.20
  5264.9 1611.41  5271.1 1612.92  5279.5 1613.50  5285.7 1615.07  5294.3 1614.70
#Mann=3,-1,0
  4694.1    0.05       0  5034.1    0.05       0  5052.9    0.05       0
Bank Sta=5034.1,5052.9
Exp/Cntr=0.3,0.1

Type RM Length L Ch R = 1,2151,102,102,102
BEGIN DESCRIPTION:
Mapping XS 41f1d1d0
END DESCRIPTION:
XS GIS Cut Line= 3
      1601976.73      6927126.44      1601905.33      6926931.14
      1601884.43      6926661.59
#Sta/Elev= 30
  4752.8 1606.66  4775.1 1605.36  4783.1 1603.76  4793.7 1603.09  4805.6 1601.28
  4825.5 1601.79  4830.8 1600.75  4836.3 1600.80  4861.3 1599.40  4868.3 1598.06
  4886.6 1596.47  4910.8 1595.40  4917.1 1594.69  4942.3 1594.14  4947.6 1595.33
  4950.3 1594.12  4950.8 1593.62  4968.6 1593.62  4969.1 1594.12  5004.0 1594.17
  5034.4 1594.88  5064.2 1597.45  5084.2 1598.39  5114.3 1599.08  5134.4 1600.29
  5159.3 1601.23  5164.5 1601.90  5174.5 1602.34  5184.5 1602.32  5231.1 1605.43
#Mann=3,-1,0
  4752.8    0.05       0  4950.3    0.03       0  4969.1    0.05       0
Bank Sta=4950.3,4969.1
Exp/Cntr=0.3,0.1

Type RM Length L Ch R = 1,2049,226,226,226
BEGIN DESCRIPTION:
Mapping XS 8f7b2ea5
END DESCRIPTION:
XS GIS Cut Line= 3
      1602056.56      6927147.51      1601980.94      6926912.24
      1601964.13      6926683.28
#Sta/Elev= 30
  4779.0 1604.99  4797.3 1604.15  4802.6 1604.53  4829.4 1603.57  4834.7 1604.07
  4861.5 1602.05  4866.8 1602.44  4893.6 1600.04  4898.9 1600.24  4904.5 1599.00
  4931.0 1595.87  4936.2 1595.89  4988.6 1593.04  5009.6 1593.17  5010.7 1592.71
  5011.2 1592.21  5029.0 1592.21  5029.5 1592.71  5030.8 1593.26  5042.2 1593.72
  5060.5 1593.46  5070.5 1593.77  5080.5 1594.68  5130.6 1597.35  5140.7 1597.33
  5170.6 1599.17  5175.7 1600.01  5200.8 1601.03  5230.9 1601.33  5255.7 1602.22
#Mann=3,-1,0
  4779.0    0.05       0  5010.7    0.03       0  5029.5    0.05       0
Bank Sta=5010.7,5029.5
Exp/Cntr=0.3,0.1

Type RM Length L Ch R = 1,1823,152,152,152
BEGIN DESCRIPTION:
Deadman 07 4.0
END DESCRIPTION:
XS GIS Cut Line= 3
      1602354.99      6926987.99      1602155.00      6926788.00
      1601904.99      6926587.99
#Sta/Elev= 30
  4718.4 1609.51  4732.5 1608.86  4746.7 1607.61  4760.8 1605.02  4775.0 1604.18
  4789.1 1601.08  4845.7 1598.07  4859.8 1597.68  4888.1 1594.24  4902.2 1591.66
  4916.4 1590.65  4930.5 1588.80  5019.8 1587.83  5020.3 1587.33  5038.1 1587.33
  5038.6 1587.83  5043.6 1589.92  5078.9 1593.24  5136.5 1596.64  5150.9 1597.70
  5157.3 1598.66  5165.3 1598.81  5179.7 1600.02  5186.1 1599.93  5200.5 1601.49
  5206.9 1601.55  5271.0 1606.36  5279.0 1607.58  5314.2 1608.59  5321.4 1608.22
#Mann=3,-1,0
  4718.4    0.05       0  5019.8    0.03       0  5038.6    0.05       0
Bank Sta=5019.8,5038.6
Exp/Cntr=0.3,0.1

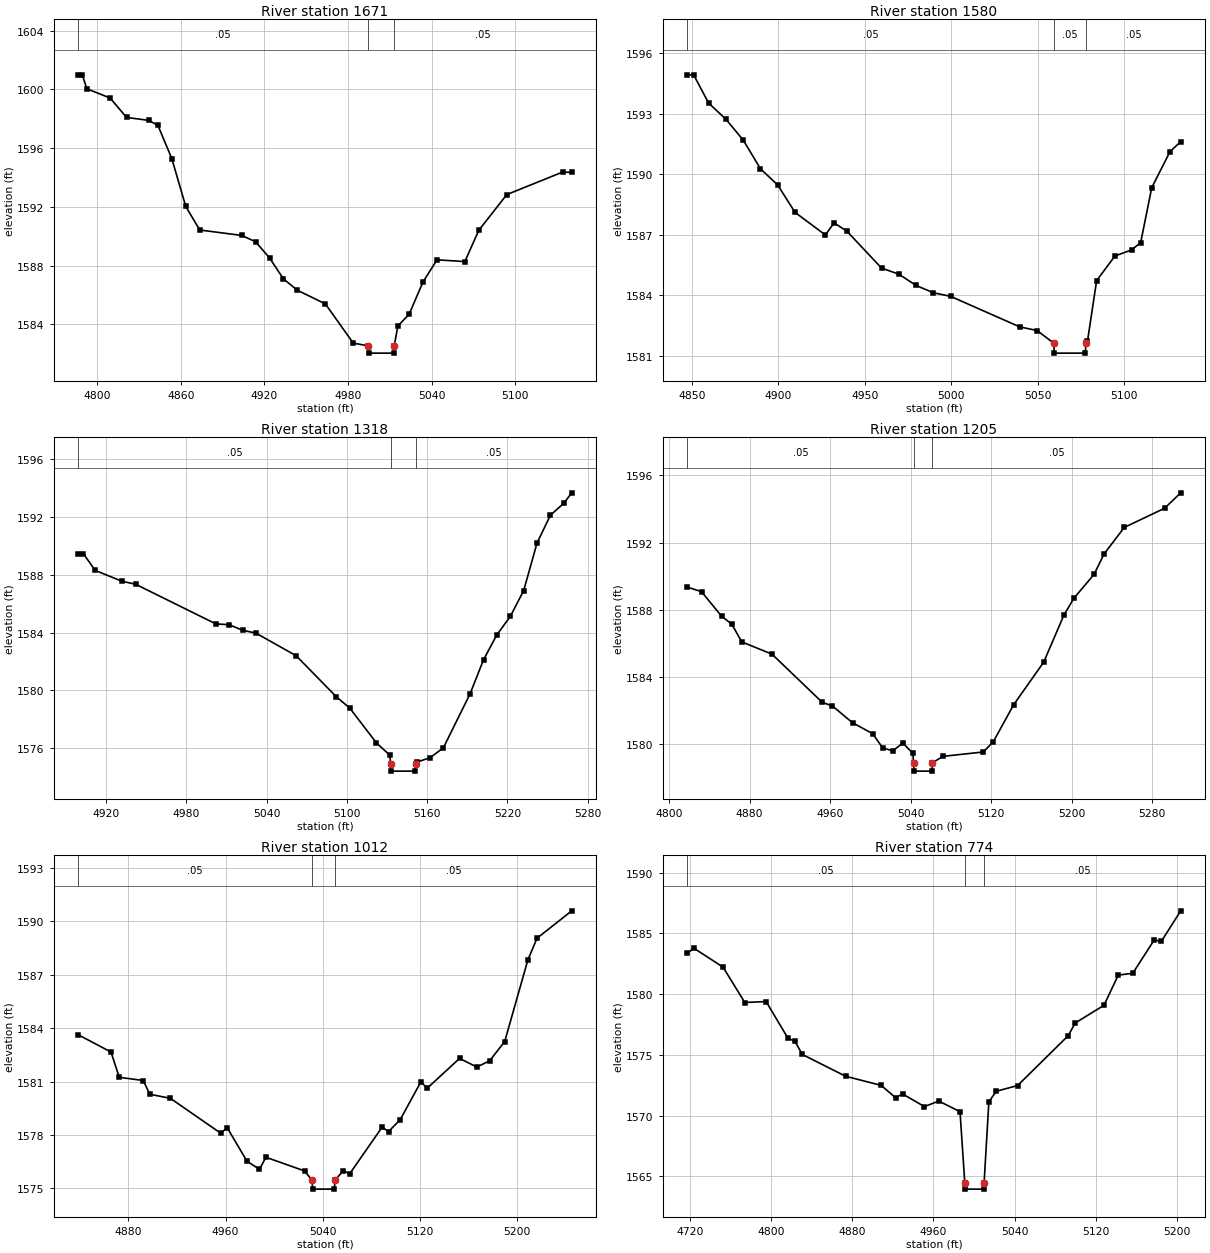
Type RM Length L Ch R = 1,1671,91,91,91
BEGIN DESCRIPTION:
Mapping XS 41fde6ee
END DESCRIPTION:
XS GIS Cut Line= 3
      1602335.88      6926895.43      1602289.68      6926874.43
      1602272.96      6926571.45
#Sta/Elev= 30
  4786.4 1600.99  4789.3 1600.99  4792.6 1600.04  4809.3 1599.41  4821.1 1598.09
  4837.0 1597.89  4843.6 1597.55  4853.6 1595.28  4863.6 1592.03  4873.6 1590.43
  4903.7 1590.06  4913.7 1589.63  4923.7 1588.53  4933.7 1587.10  4943.7 1586.33
  4963.8 1585.40  4983.8 1582.73  4994.4 1582.55  4994.9 1582.05  5012.7 1582.05
  5013.2 1582.55  5015.8 1583.89  5023.9 1584.70  5033.9 1586.90  5043.9 1588.40
  5063.9 1588.28  5073.9 1590.41  5094.0 1592.84  5134.0 1594.37  5140.6 1594.35
#Mann=3,-1,0
  4786.4    0.05       0  4994.4    0.03       0  5013.2    0.05       0
Bank Sta=4994.4,5013.2
Exp/Cntr=0.3,0.1

Type RM Length L Ch R = 1,1580,262,262,262
BEGIN DESCRIPTION:
Mapping XS 32178ef1
END DESCRIPTION:
XS GIS Cut Line= 3
      1602356.61      6926830.36      1602365.87      6926605.07
      1602309.16      6926584.81
#Sta/Elev= 30
  4847.2 1594.92  4850.9 1594.92  4859.6 1593.52  4869.6 1592.72  4879.6 1591.69
  4889.6 1590.27  4899.6 1589.46  4909.6 1588.11  4927.2 1586.99  4932.2 1587.59
  4939.6 1587.18  4959.7 1585.35  4969.7 1585.05  4979.7 1584.49  4989.7 1584.13
  4999.7 1583.95  5039.7 1582.44  5049.7 1582.26  5059.3 1581.64  5059.8 1581.14
  5077.6 1581.14  5078.1 1581.64  5078.9 1581.72  5084.2 1584.73  5094.8 1585.95
  5104.4 1586.25  5109.7 1586.61  5116.1 1589.33  5126.7 1591.12  5132.9 1591.61
#Mann=3,-1,0
  4847.2    0.05       0  5059.3    0.05       0  5078.1    0.05       0
Bank Sta=5059.3,5078.1
Exp/Cntr=0.3,0.1

Type RM Length L Ch R = 1,1318,113,113,113
BEGIN DESCRIPTION:
Mapping XS 4787e774
END DESCRIPTION:
XS GIS Cut Line= 2
      1602667.75      6926574.09      1602299.07      6926578.28
#Sta/Elev= 30
  4899.3 1589.44  4903.2 1589.44  4912.0 1588.29  4932.1 1587.54  4942.1 1587.34
  5002.1 1584.60  5012.1 1584.54  5022.1 1584.16  5032.1 1583.96  5062.1 1582.40
  5092.1 1579.57  5102.1 1578.79  5122.1 1576.38  5132.1 1575.53  5132.7 1574.93
  5133.2 1574.43  5151.0 1574.43  5151.5 1574.93  5152.1 1575.05  5162.1 1575.35
  5172.1 1576.04  5192.1 1579.78  5202.1 1582.12  5212.1 1583.85  5222.1 1585.11
  5232.1 1586.90  5242.1 1590.19  5252.1 1592.11  5262.1 1592.93  5268.0 1593.65
#Mann=3,-1,0
  4899.3    0.05       0  5132.7    0.05       0  5151.5    0.05       0
Bank Sta=5132.7,5151.5
Exp/Cntr=0.3,0.1

Type RM Length L Ch R = 1,1205,193,193,193
BEGIN DESCRIPTION:
Mapping XS e8c9942b
END DESCRIPTION:
XS GIS Cut Line= 2
      1602739.16      6926487.98      1602248.88      6926492.17
#Sta/Elev= 30
  4818.0 1589.35  4832.2 1589.08  4852.2 1587.61  4862.2 1587.15  4872.2 1586.09
  4902.2 1585.36  4952.2 1582.49  4962.2 1582.28  4982.2 1581.28  5002.2 1580.63
  5012.2 1579.78  5022.2 1579.61  5032.2 1580.07  5042.2 1579.46  5042.8 1578.90
  5043.3 1578.40  5061.1 1578.40  5061.6 1578.90  5072.2 1579.28  5112.2 1579.54
  5122.2 1580.16  5142.2 1582.34  5172.2 1584.89  5192.2 1587.68  5202.2 1588.69
  5222.2 1590.11  5232.2 1591.33  5252.2 1592.90  5292.2 1594.04  5308.3 1594.96
#Mann=3,-1,0
  4818.0    0.05       0  5042.8    0.05       0  5061.6    0.05       0
Bank Sta=5042.8,5061.6
Exp/Cntr=0.3,0.1

Type RM Length L Ch R = 1,1012,238,238,238
BEGIN DESCRIPTION:
Mapping XS ae700b57
END DESCRIPTION:
XS GIS Cut Line= 2
      1602697.13      6926380.87      1602310.66      6926254.84
#Sta/Elev= 30
  4838.6 1583.63  4865.6 1582.66  4872.4 1581.24  4892.2 1581.06  4897.5 1580.29
  4914.5 1580.06  4956.0 1578.10  4961.3 1578.41  4977.6 1576.53  4987.9 1576.07
  4993.2 1576.75  5025.1 1575.98  5031.2 1575.46  5031.7 1574.96  5049.6 1574.96
  5050.1 1575.46  5057.0 1576.00  5062.2 1575.82  5088.9 1578.44  5094.2 1578.19
  5103.8 1578.86  5120.8 1580.98  5126.1 1580.63  5152.7 1582.30  5166.9 1581.82
  5177.4 1582.16  5189.9 1583.25  5209.0 1587.84  5216.5 1589.05  5245.1 1590.59
#Mann=3,-1,0
  4838.6    0.05       0  5031.2    0.03       0  5050.1    0.05       0
Bank Sta=5031.2,5050.1
Exp/Cntr=0.3,0.1

Type RM Length L Ch R = 1,774,253,253,253
BEGIN DESCRIPTION:
Mapping XS 53e179ff
END DESCRIPTION:
XS GIS Cut Line= 2
      1602800.01      6926343.02      1602469.08      6925986.96
#Sta/Elev= 30
  4717.6 1583.40  4724.5 1583.76  4752.8 1582.23  4774.3 1579.31  4795.3 1579.39
  4816.8 1576.37  4823.6 1576.12  4831.0 1575.03  4873.5 1573.24  4908.7 1572.48
  4922.8 1571.47  4929.7 1571.78  4951.2 1570.74  4965.4 1571.19  4986.3 1570.32
  4991.0 1564.44  4991.5 1563.94  5009.5 1563.94  5010.0 1564.44  5014.7 1571.13
  5022.0 1572.00  5043.0 1572.47  5092.9 1576.58  5099.7 1577.62  5128.1 1579.08
  5142.2 1581.57  5156.4 1581.71  5177.4 1584.44  5184.7 1584.36  5203.7 1586.86
#Mann=3,-1,0
  4717.6    0.05       0  4991.0    0.03       0  5010.0    0.05       0
Bank Sta=4991,5010
Exp/Cntr=0.3,0.1

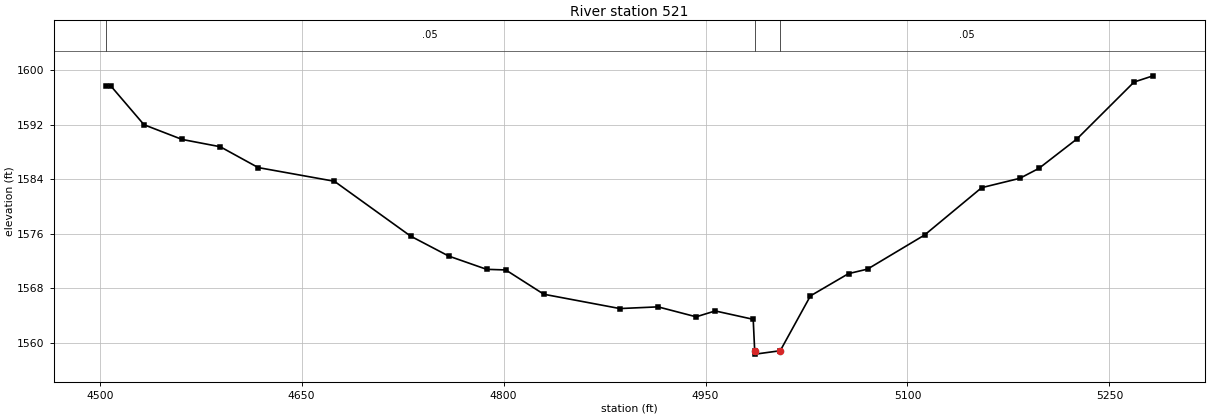
Type RM Length L Ch R = 1,521,0,0,0
BEGIN DESCRIPTION:
Deadman 07 1.0
END DESCRIPTION:
XS GIS Cut Line= 3
      1603155.00      6926338.00      1602805.00      6925988.00
      1602605.02      6925788.02
#Sta/Elev= 30
  4504.6 1597.73  4508.1 1597.73  4532.9 1592.00  4561.2 1589.84  4589.5 1588.77
  4617.7 1585.71  4674.3 1583.70  4730.9 1575.65  4759.2 1572.72  4787.4 1570.77
  4801.6 1570.68  4829.9 1567.11  4886.4 1565.01  4914.7 1565.26  4943.0 1563.80
  4957.2 1564.66  4985.4 1563.43  4986.5 1558.82  4987.0 1558.32  5005.5 1558.82
  5027.9 1566.87  5056.2 1570.14  5070.3 1570.80  5112.7 1575.81  5155.1 1582.76
  5183.4 1584.13  5197.6 1585.59  5225.9 1589.92  5268.3 1598.27  5282.4 1599.18
#Mann=3,-1,0
  4504.6    0.05       0  4986.5    0.05       0  5005.5    0.05       0
Bank Sta=4986.5,5005.5
Exp/Cntr=0.3,0.1

Chan Stop Cuts=-1