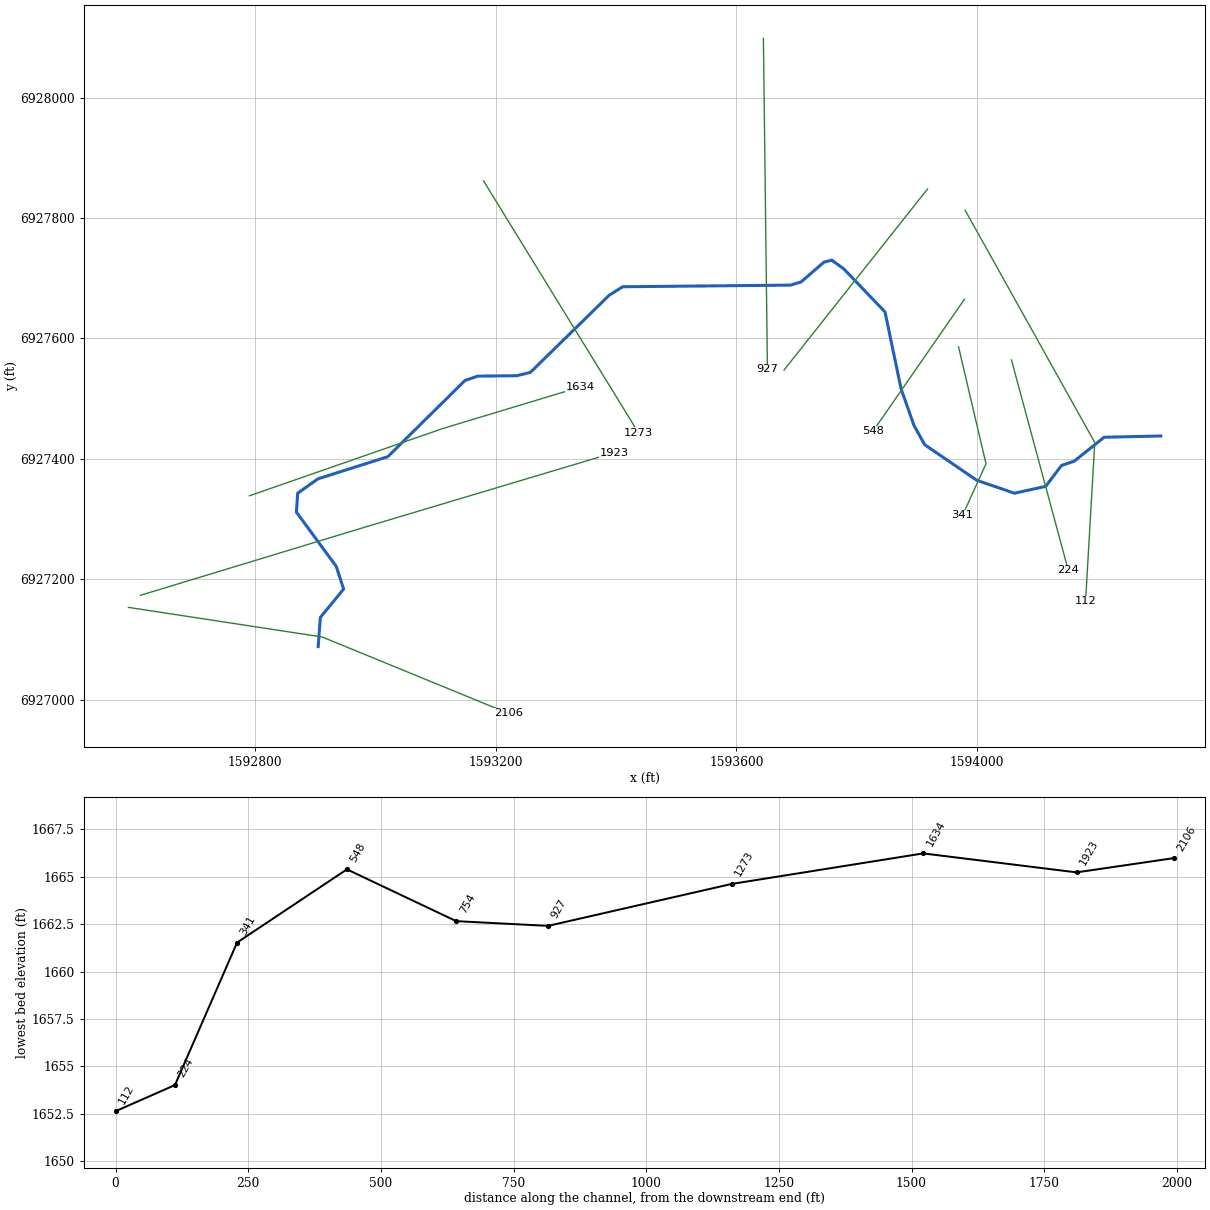
--- Deadman 08.prj (project) ---

Proj Title=Deadman 08 Base Level Engineering
Current Plan=p01
Default Exp/Contr=0.3,0.1
English Units
Geom File=g01
Flow File=f01
Plan File=p01
BEGIN DESCRIPTION:
Deadman 08
END DESCRIPTION:

--- Deadman 08.p01 (plan) ---

Plan Title=Multiple Run
Short Identifier=Multiple
Geom File=g01
Flow File=f01
Subcritical Flow
K Sum by GR= 0
Std Step Tol= 0.01
Critical Tol= 0.01
Num of Std Step Trials= 20
Max Error Tol= 0.3
Flow Tol Ratio= 0.001
Split Flow NTrial= 30
Split Flow Tol= 0.02
Split Flow Ratio= 0.02
Log Output Level= 0
Friction Slope Method= 1
Unsteady Friction Slope Method= 2
Unsteady Bridges Friction Slope Method= 1
Parabolic Critical Depth
Global Vel Dist=  1 , 1 , 1
Global Log Level= 0
CheckData=True
Encroach Param= -1, 0, 0, 0
BEGIN DESCRIPTION:
Multiple Run
END DESCRIPTION:

--- Deadman 08.f01 (steady flow) ---

Flow Title=Multiple
Number of Profiles=7
Profile Names=10-year,25-year,50-year,1pct_min,100-year,1pct_plu,500-year
River Rch & RM= Deadman 08,Reach-1,2106
     112     143     166      96     192     383     259
River Rch & RM= Deadman 08,Reach-1,1923
     135     174     204     119     238     475     327
Boundary for River Rch & Prof#=Deadman 08,Reach-1,1
Up Type=0
Dn Type=3
Dn Slope=0.005
Boundary for River Rch & Prof#=Deadman 08,Reach-1,2
Up Type=0
Dn Type=3
Dn Slope=0.005
Boundary for River Rch & Prof#=Deadman 08,Reach-1,3
Up Type=0
Dn Type=3
Dn Slope=0.005
Boundary for River Rch & Prof#=Deadman 08,Reach-1,4
Up Type=0
Dn Type=3
Dn Slope=0.005
Boundary for River Rch & Prof#=Deadman 08,Reach-1,5
Up Type=0
Dn Type=3
Dn Slope=0.005
Boundary for River Rch & Prof#=Deadman 08,Reach-1,6
Up Type=0
Dn Type=3
Dn Slope=0.005
Boundary for River Rch & Prof#=Deadman 08,Reach-1,7
Up Type=0
Dn Type=3
Dn Slope=0.005

--- Deadman 08.g01 (geometry) ---

Geom Title=Existing Conditions

River Reach=Deadman 08,Reach-1
Reach XY= 30
      1592905.00      6927088.00      1592908.60      6927136.51
      1592947.28      6927183.63      1592934.97      6927221.39
      1592868.78      6927311.45      1592870.95      6927342.92
      1592904.59      6927366.79      1593020.56      6927403.50
      1593148.83      6927530.14      1593170.22      6927537.47
      1593234.94      6927538.13      1593257.43      6927543.52
      1593388.24      6927671.57      1593410.85      6927685.94
      1593689.84      6927688.66      1593707.45      6927694.03
      1593745.16      6927726.67      1593758.43      6927730.21
      1593778.41      6927715.57      1593846.84      6927644.09
      1593873.48      6927516.41      1593894.95      6927455.60
      1593912.83      6927423.40      1593999.28      6927364.38
      1594061.87      6927342.92      1594113.74      6927354.25
      1594140.02      6927388.97      1594161.05      6927396.04
      1594210.87      6927435.89      1594305.00      6927438.00

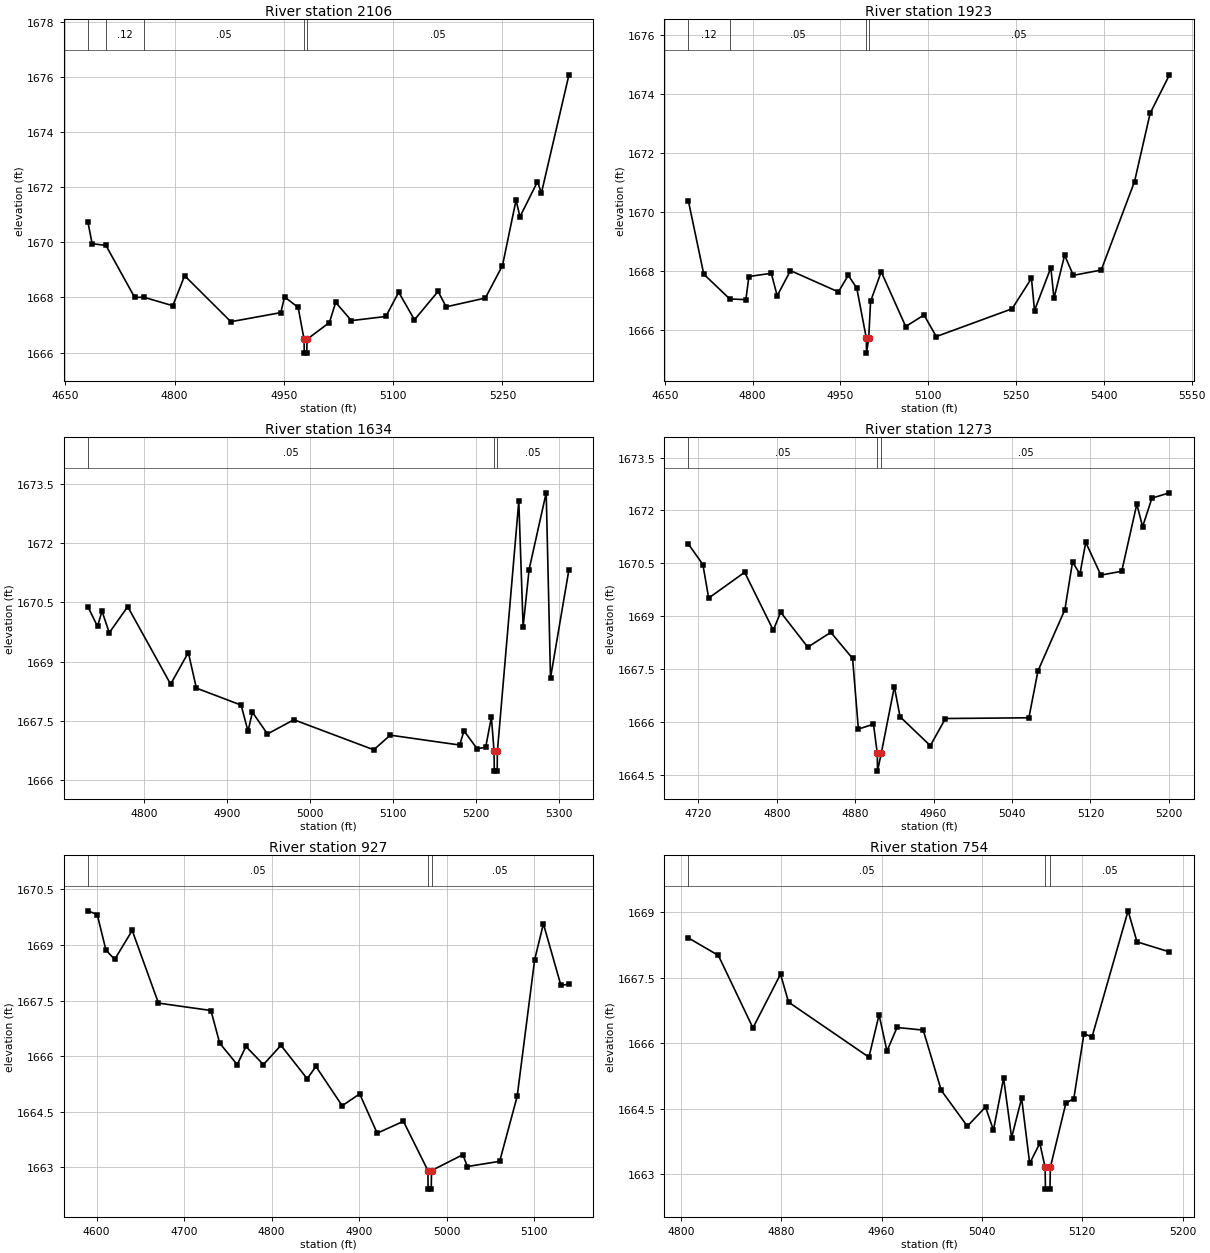
Type RM Length L Ch R = 1,2106,183,183,183
BEGIN DESCRIPTION:
Deadman 08 2.0
END DESCRIPTION:
XS GIS Cut Line= 3
      1592589.71      6927153.22      1592911.59      6927104.04
      1593221.16      6926977.09
#Sta/Elev= 30
  4681.0 1670.75  4686.9 1669.95  4705.8 1669.89  4745.3 1668.00  4757.7 1668.01
  4797.6 1667.70  4813.8 1668.79  4877.3 1667.12  4945.8 1667.45  4950.9 1668.02
  4969.6 1667.64  4977.7 1666.48  4978.0 1665.98  4981.5 1665.98  4981.7 1666.48
  5012.5 1667.09  5021.1 1667.82  5042.7 1667.16  5089.9 1667.31  5107.6 1668.19
  5129.2 1667.19  5161.6 1668.22  5172.7 1667.66  5226.5 1667.98  5250.0 1669.16
  5268.6 1671.53  5274.0 1670.93  5298.0 1672.20  5303.4 1671.79  5341.2 1676.08
#Mann=5,-1,0
  4681.0    0.05       0  4705.8    0.12       0  4757.7    0.05       0
  4977.7    0.03       0  4981.7    0.05       0
Bank Sta=4977.7,4981.7
Exp/Cntr=0.3,0.1

Type RM Length L Ch R = 1,1923,289,289,289
BEGIN DESCRIPTION:
Mapping XS 940416b9
END DESCRIPTION:
XS GIS Cut Line= 3
      1592609.81      6927173.32      1592985.35      6927287.32
      1593396.61      6927410.25
#Sta/Elev= 30
  4690.4 1670.38  4716.7 1667.90  4761.2 1667.06  4788.6 1667.04  4793.8 1667.82
  4832.0 1667.93  4842.1 1667.17  4864.8 1668.02  4946.6 1667.30  4963.5 1667.86
  4978.0 1667.43  4994.4 1665.73  4994.6 1665.23  4998.4 1665.73  5001.6 1666.98
  5019.8 1667.98  5061.6 1666.13  5092.9 1666.52  5113.8 1665.79  5243.3 1666.73
  5276.4 1667.76  5281.6 1666.67  5309.5 1668.12  5314.8 1667.08  5333.0 1668.54
  5347.9 1667.86  5395.6 1668.04  5452.4 1671.03  5479.1 1673.34  5512.1 1674.64
#Mann=4,-1,0
  4690.4    0.12       0  4761.2    0.05       0  4994.4    0.03       0
  4998.4    0.05       0
Bank Sta=4994.4,4998.4
Exp/Cntr=0.3,0.1

Type RM Length L Ch R = 1,1634,361,361,361
BEGIN DESCRIPTION:
Mapping XS 1f40c91e
END DESCRIPTION:
XS GIS Cut Line= 3
      1592790.68      6927338.58      1593111.84      6927450.34
      1593340.97      6927519.51
#Sta/Elev= 30
  4732.1 1670.39  4743.8 1669.89  4749.1 1670.28  4757.9 1669.73  4780.1 1670.39
  4831.8 1668.43  4853.1 1669.23  4862.8 1668.33  4916.7 1667.90  4925.0 1667.24
  4930.3 1667.72  4948.4 1667.17  4980.2 1667.53  5076.4 1666.77  5096.3 1667.14
  5179.9 1666.89  5185.1 1667.25  5200.8 1666.80  5211.2 1666.83  5218.1 1667.60
  5221.3 1666.73  5221.6 1666.23  5225.1 1666.23  5225.3 1666.73  5251.1 1673.06
  5256.3 1669.88  5263.5 1671.33  5284.1 1673.27  5289.3 1668.59  5311.5 1671.33
#Mann=3,-1,0
  4732.1    0.05       0  5221.3    0.05       0  5225.3    0.05       0
Bank Sta=5221.3,5225.3
Exp/Cntr=0.3,0.1

Type RM Length L Ch R = 1,1273,346,346,346
BEGIN DESCRIPTION:
Mapping XS e5111bff
END DESCRIPTION:
XS GIS Cut Line= 2
      1593179.83      6927861.74      1593436.88      6927443.76
#Sta/Elev= 30
  4709.9 1671.05  4724.7 1670.47  4730.6 1669.52  4767.3 1670.25  4796.5 1668.61
  4804.0 1669.12  4831.7 1668.13  4855.2 1668.55  4877.4 1667.81  4883.3 1665.81
  4898.7 1665.95  4902.6 1665.12  4902.8 1664.62  4906.6 1665.12  4920.0 1667.01
  4925.8 1666.16  4956.7 1665.34  4972.1 1666.11  5057.2 1666.13  5066.5 1667.46
  5093.9 1669.19  5101.7 1670.54  5109.3 1670.20  5115.2 1671.10  5130.6 1670.17
  5151.9 1670.28  5167.3 1672.18  5173.2 1671.54  5182.7 1672.35  5200.6 1672.50
#Mann=3,-1,0
  4709.9    0.05       0  4902.6    0.05       0  4906.6    0.05       0
Bank Sta=4902.6,4906.6
Exp/Cntr=0.3,0.1

Type RM Length L Ch R = 1,927,173,173,173
BEGIN DESCRIPTION:
Mapping XS 5c1c151d
END DESCRIPTION:
XS GIS Cut Line= 2
      1593644.74      6928098.71      1593651.44      6927548.85
#Sta/Elev= 30
  4589.9 1669.92  4600.6 1669.82  4610.6 1668.86  4620.6 1668.61  4640.6 1669.39
  4670.6 1667.43  4730.6 1667.23  4740.6 1666.35  4760.6 1665.77  4770.6 1666.26
  4790.6 1665.77  4810.6 1666.29  4840.6 1665.39  4850.6 1665.72  4880.6 1664.66
  4900.6 1664.98  4920.6 1663.92  4950.6 1664.24  4978.6 1662.91  4978.8 1662.41
  4982.4 1662.41  4982.7 1662.91  5018.6 1663.34  5023.6 1663.02  5060.6 1663.16
  5080.6 1664.91  5100.6 1668.60  5110.6 1669.57  5130.6 1667.91  5139.8 1667.94
#Mann=3,-1,0
  4589.9    0.05       0  4978.6    0.05       0  4982.7    0.05       0
Bank Sta=4978.6,4982.7
Exp/Cntr=0.3,0.1

Type RM Length L Ch R = 1,754,206,206,206
BEGIN DESCRIPTION:
Mapping XS 95f2544e
END DESCRIPTION:
XS GIS Cut Line= 2
      1593917.45      6927848.39      1593679.12      6927547.68
#Sta/Elev= 30
  4805.9 1668.41  4829.8 1668.01  4857.4 1666.35  4879.4 1667.58  4885.8 1666.94
  4949.9 1665.68  4958.0 1666.65  4964.3 1665.82  4972.3 1666.36  4993.2 1666.30
  5007.6 1664.92  5028.4 1664.10  5042.9 1664.54  5049.2 1664.01  5057.3 1665.20
  5063.7 1663.84  5071.7 1664.74  5078.1 1663.25  5086.2 1663.71  5090.4 1663.16
  5090.7 1662.66  5094.3 1662.66  5094.6 1663.16  5107.0 1664.63  5113.3 1664.73
  5121.4 1666.22  5127.8 1666.14  5156.6 1669.03  5163.7 1668.32  5189.6 1668.09
#Mann=3,-1,0
  4805.9    0.05       0  5090.4    0.05       0  5094.6    0.05       0
Bank Sta=5090.4,5094.6
Exp/Cntr=0.3,0.1

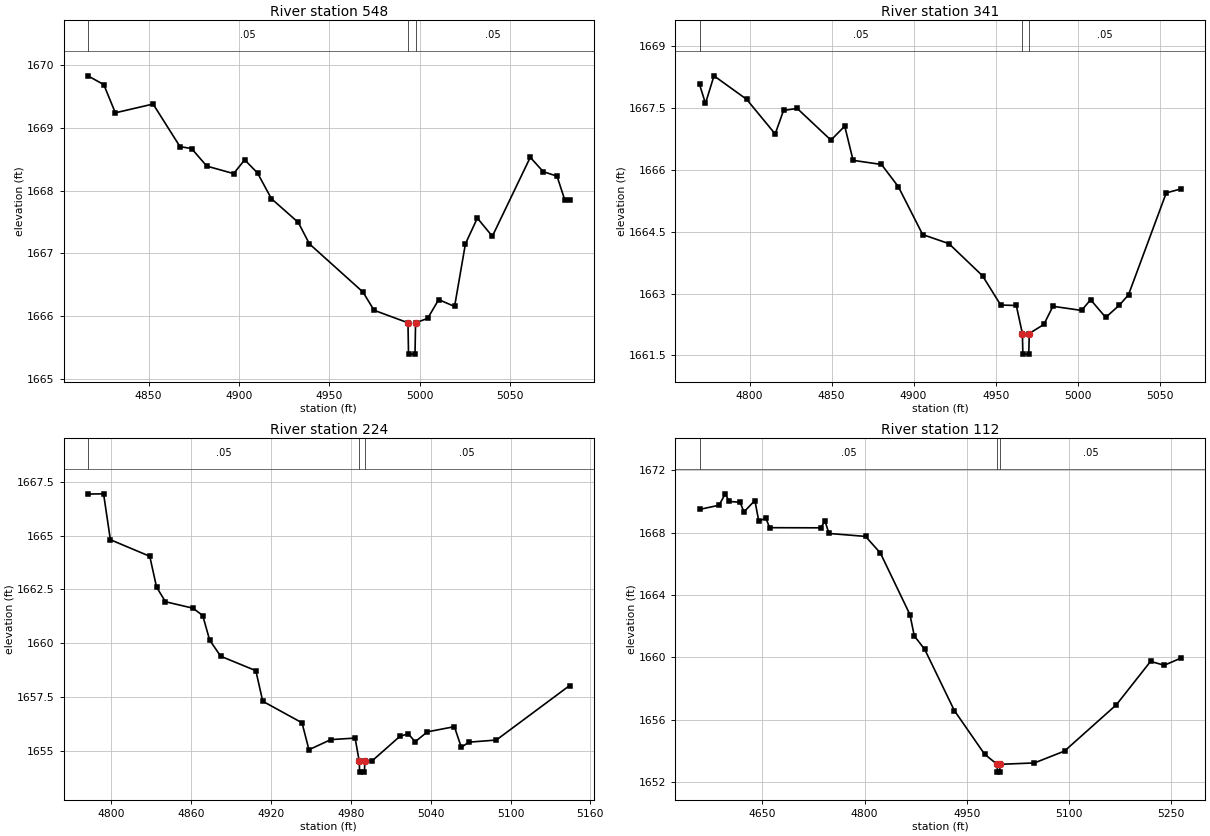
Type RM Length L Ch R = 1,548,207,207,207
BEGIN DESCRIPTION:
Mapping XS 49691f9d
END DESCRIPTION:
XS GIS Cut Line= 2
      1593978.81      6927665.19      1593826.89      6927445.99
#Sta/Elev= 30
  4816.4 1669.83  4825.2 1669.69  4831.6 1669.24  4852.5 1669.38  4867.4 1668.70
  4873.8 1668.67  4882.2 1668.39  4897.1 1668.27  4903.2 1668.49  4910.3 1668.28
  4918.0 1667.87  4932.9 1667.49  4939.0 1667.15  4968.7 1666.38  4974.8 1666.09
  4993.6 1665.89  4993.9 1665.39  4997.5 1665.39  4997.8 1665.89  5004.5 1665.96
  5010.6 1666.26  5019.4 1666.15  5025.4 1667.15  5032.0 1667.56  5040.3 1667.27
  5061.3 1668.53  5068.5 1668.30  5076.1 1668.23  5080.4 1667.85  5083.1 1667.85
#Mann=3,-1,0
  4816.4    0.05       0  4993.6    0.03       0  4997.8    0.05       0
Bank Sta=4993.6,4997.8
Exp/Cntr=0.3,0.1

Type RM Length L Ch R = 1,341,117,117,117
BEGIN DESCRIPTION:
Mapping XS 81e33d12
END DESCRIPTION:
XS GIS Cut Line= 3
      1593969.04      6927585.97      1594014.61      6927391.74
      1593975.55      6927306.02
#Sta/Elev= 30
  4769.5 1668.07  4773.1 1667.61  4778.3 1668.28  4798.2 1667.71  4815.6 1666.87
  4820.7 1667.44  4829.0 1667.49  4849.6 1666.72  4858.0 1667.06  4863.1 1666.23
  4880.4 1666.13  4890.7 1665.59  4905.5 1664.43  4921.5 1664.21  4942.0 1663.43
  4953.1 1662.72  4962.6 1662.71  4966.3 1662.03  4966.6 1661.53  4970.2 1661.53
  4970.5 1662.03  4979.4 1662.25  4984.9 1662.69  5002.4 1662.59  5007.9 1662.85
  5017.1 1662.42  5025.5 1662.72  5031.0 1662.97  5054.0 1665.44  5063.2 1665.54
#Mann=3,-1,0
  4769.5    0.05       0  4966.3    0.03       0  4970.5    0.05       0
Bank Sta=4966.3,4970.5
Exp/Cntr=0.3,0.1

Type RM Length L Ch R = 1,224,112,112,112
BEGIN DESCRIPTION:
Mapping XS ed39c9a9
END DESCRIPTION:
XS GIS Cut Line= 2
      1594056.92      6927564.30      1594151.34      6927214.83
#Sta/Elev= 30
  4782.4 1666.93  4794.2 1666.94  4799.3 1664.81  4828.9 1664.04  4834.0 1662.61
  4840.7 1661.93  4861.4 1661.63  4868.7 1661.29  4873.9 1660.15  4882.2 1659.40
  4908.6 1658.73  4913.8 1657.31  4943.3 1656.31  4948.5 1655.06  4965.0 1655.53
  4983.2 1655.60  4986.3 1654.52  4986.6 1654.02  4990.2 1654.02  4990.5 1654.52
  4996.1 1654.55  5016.8 1655.68  5023.1 1655.80  5028.3 1655.43  5037.5 1655.89
  5057.8 1656.13  5063.0 1655.17  5068.6 1655.41  5089.3 1655.51  5144.4 1658.04
#Mann=3,-1,0
  4782.4    0.05       0  4986.3    0.03       0  4990.5    0.05       0
Bank Sta=4986.3,4990.5
Exp/Cntr=0.3,0.1

Type RM Length L Ch R = 1,112,0,0,0
BEGIN DESCRIPTION:
Deadman 08 1.0
END DESCRIPTION:
XS GIS Cut Line= 3
      1593980.00      6927813.01      1594195.35      6927427.14
      1594180.00      6927162.98
#Sta/Elev= 30
  4558.1 1669.48  4586.7 1669.75  4595.8 1670.48  4601.5 1669.99  4617.5 1669.94
  4623.2 1669.32  4639.2 1670.05  4645.0 1668.72  4655.2 1668.93  4660.9 1668.31
  4735.6 1668.30  4742.1 1668.73  4747.8 1667.94  4801.5 1667.75  4823.2 1666.69
  4866.6 1662.74  4873.0 1661.37  4888.3 1660.51  4931.7 1656.59  4976.1 1653.79
  4994.5 1653.14  4994.8 1652.64  4998.4 1652.64  4998.7 1653.14  5049.2 1653.23
  5093.3 1653.99  5169.4 1656.96  5219.5 1659.74  5239.5 1659.49  5264.6 1659.96
#Mann=3,-1,0
  4558.1    0.05       0  4994.5    0.03       0  4998.7    0.05       0
Bank Sta=4994.5,4998.7
Exp/Cntr=0.3,0.1

Chan Stop Cuts=-1