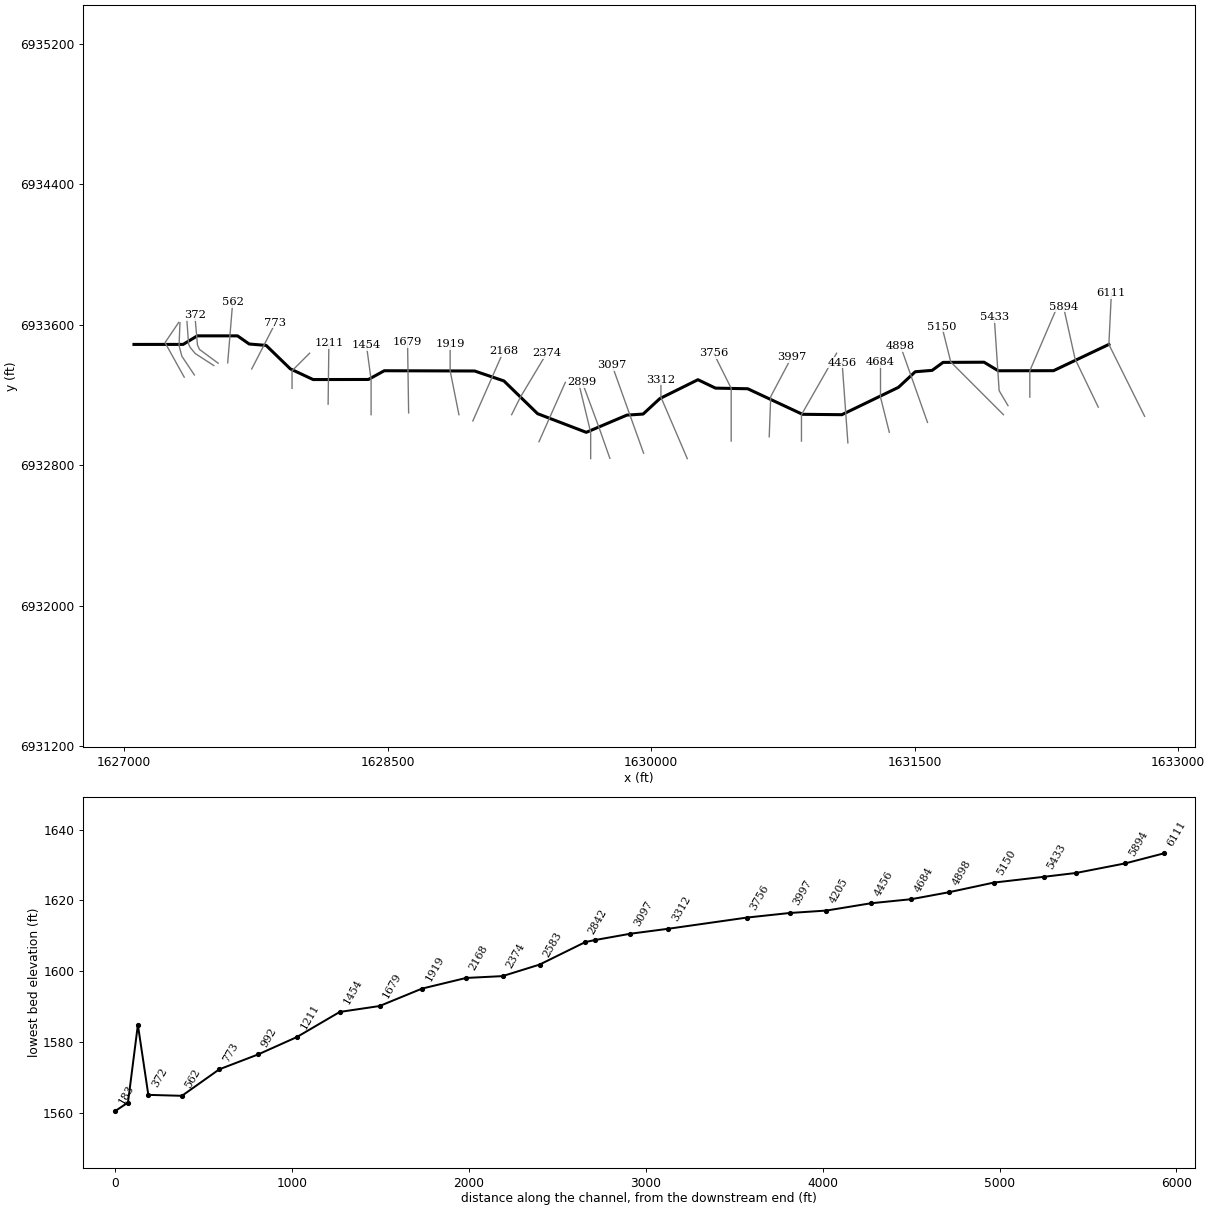
--- Deadman 09.prj (project) ---

Proj Title=Deadman 09 Base Level Engineering
Current Plan=p01
Default Exp/Contr=0.3,0.1
English Units
Geom File=g01
Flow File=f01
Plan File=p01
BEGIN DESCRIPTION:
Deadman 09
END DESCRIPTION:

--- Deadman 09.p01 (plan) ---

Plan Title=Multiple Run
Short Identifier=Multiple
Geom File=g01
Flow File=f01
Subcritical Flow
K Sum by GR= 0
Std Step Tol= 0.01
Critical Tol= 0.01
Num of Std Step Trials= 20
Max Error Tol= 0.3
Flow Tol Ratio= 0.001
Split Flow NTrial= 30
Split Flow Tol= 0.02
Split Flow Ratio= 0.02
Log Output Level= 0
Friction Slope Method= 1
Unsteady Friction Slope Method= 2
Unsteady Bridges Friction Slope Method= 1
Parabolic Critical Depth
Global Vel Dist=  1 , 1 , 1
Global Log Level= 0
CheckData=True
Encroach Param= -1, 0, 0, 0
BEGIN DESCRIPTION:
Multiple Run
END DESCRIPTION:

--- Deadman 09.f01 (steady flow) ---

Flow Title=Multiple
Number of Profiles=7
Profile Names=10-year,25-year,50-year,1pct_min,100-year,1pct_plu,500-year
River Rch & RM= Deadman 09,Reach-1,6111
     243     334     409     250     498     994     747
River Rch & RM= Deadman 09,Reach-1,5894
     342     481     598     370     738    1472    1138
Boundary for River Rch & Prof#=Deadman 09,Reach-1,1
Up Type=0
Dn Type=3
Dn Slope=0.005
Boundary for River Rch & Prof#=Deadman 09,Reach-1,2
Up Type=0
Dn Type=3
Dn Slope=0.005
Boundary for River Rch & Prof#=Deadman 09,Reach-1,3
Up Type=0
Dn Type=3
Dn Slope=0.005
Boundary for River Rch & Prof#=Deadman 09,Reach-1,4
Up Type=0
Dn Type=3
Dn Slope=0.005
Boundary for River Rch & Prof#=Deadman 09,Reach-1,5
Up Type=0
Dn Type=3
Dn Slope=0.005
Boundary for River Rch & Prof#=Deadman 09,Reach-1,6
Up Type=0
Dn Type=3
Dn Slope=0.005
Boundary for River Rch & Prof#=Deadman 09,Reach-1,7
Up Type=0
Dn Type=3
Dn Slope=0.005

--- Deadman 09.g01 (geometry) ---

Geom Title=Existing Conditions

River Reach=Deadman 09,Reach-1
Reach XY= 30
      1632605.00      6933488.00      1632289.79      6933338.51
      1631975.03      6933338.07      1631894.50      6933386.78
      1631660.94      6933385.74      1631599.02      6933340.36
      1631502.58      6933332.46      1631407.29      6933243.85
      1631084.97      6933088.06      1630860.93      6933090.24
      1630549.06      6933235.74      1630365.50      6933239.24
      1630265.68      6933287.25      1630048.95      6933179.84
      1629953.50      6933091.62      1629860.98      6933085.64
      1629630.00      6932987.60      1629352.70      6933093.83
      1629161.17      6933280.14      1628994.50      6933336.78
      1628479.92      6933338.20      1628389.78      6933288.52
      1628075.03      6933288.06      1627945.32      6933348.76
      1627807.43      6933482.48      1627710.98      6933490.36
      1627644.50      6933536.78      1627415.50      6933536.78
      1627334.97      6933488.07      1627055.00      6933488.00

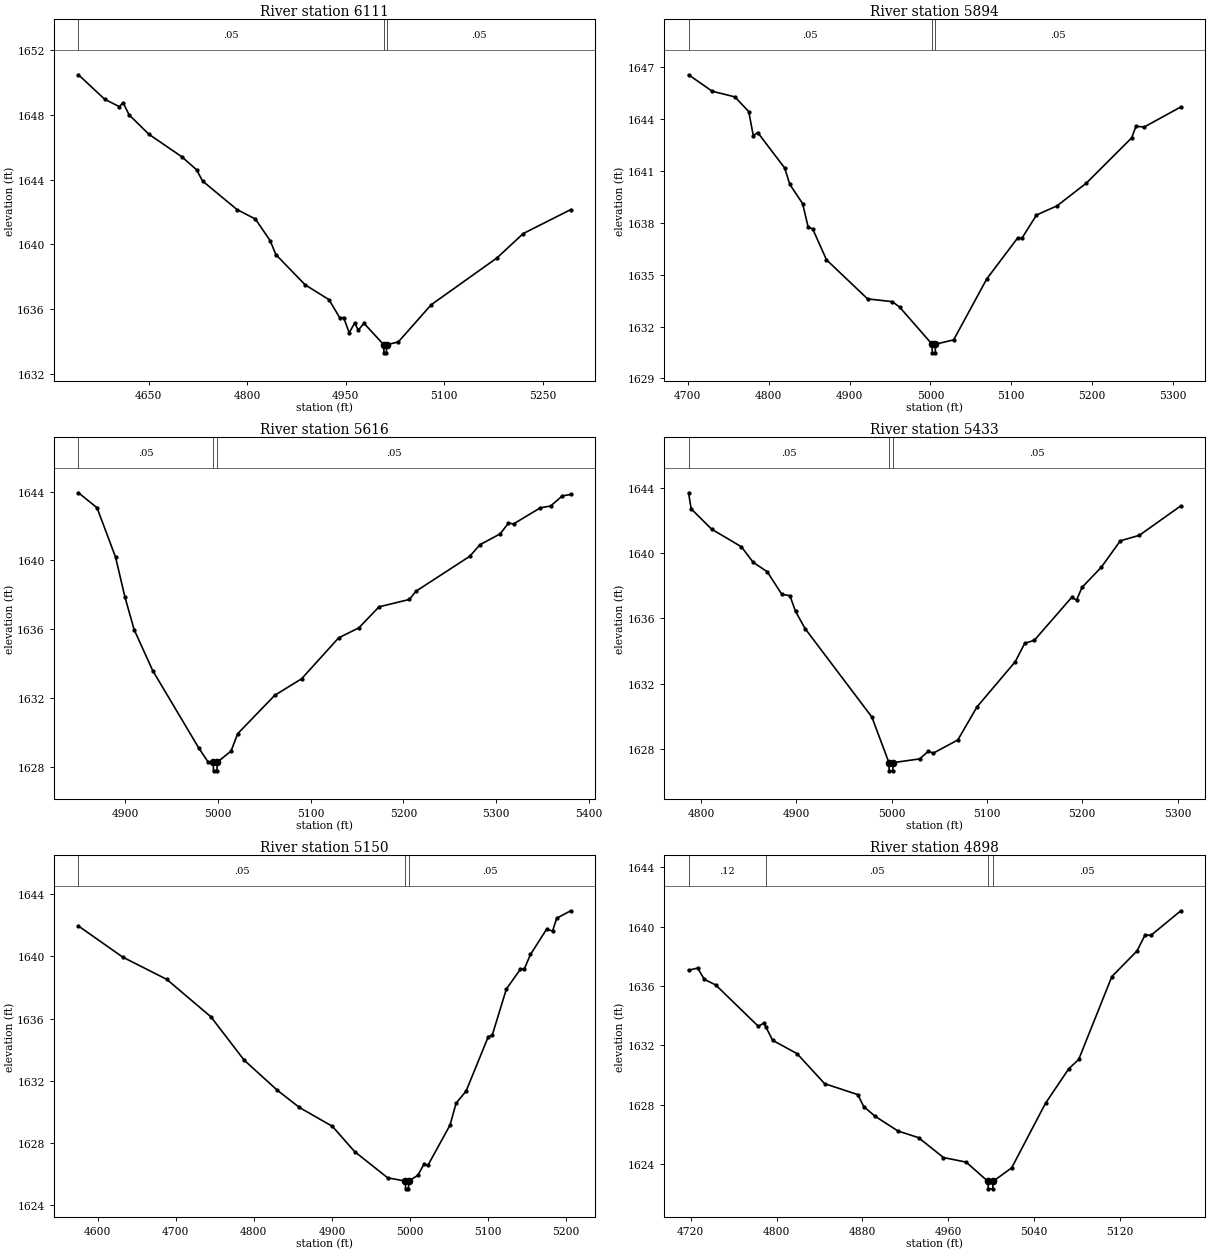
Type RM Length L Ch R = 1,6111,217,217,217
BEGIN DESCRIPTION:
Deadman 09 13.0
END DESCRIPTION:
XS GIS Cut Line= 3
      1632808.58      6933078.85      1632605.00      6933488.00
      1632619.34      6933780.25
#Sta/Elev= 30
  4543.0 1650.48  4582.9 1648.97  4605.3 1648.51  4610.9 1648.76  4620.2 1648.00
  4650.1 1646.81  4700.5 1645.41  4722.9 1644.61  4731.9 1643.92  4784.5 1642.15
  4812.4 1641.57  4834.8 1640.24  4843.6 1639.37  4888.3 1637.50  4924.4 1636.59
  4941.2 1635.45  4946.8 1635.48  4955.3 1634.54  4963.6 1635.14  4969.2 1634.70
  4977.7 1635.13  5007.9 1633.80  5008.2 1633.30  5011.9 1633.30  5012.1 1633.80
  5030.0 1633.97  5080.1 1636.27  5180.2 1639.16  5220.3 1640.67  5292.6 1642.15
#Mann=3,-1,0
  4543.0    0.05       0  5007.9    0.05       0  5012.1    0.05       0
Bank Sta=5007.9,5012.1
Exp/Cntr=0.3,0.1

Type RM Length L Ch R = 1,5894,278,278,278
BEGIN DESCRIPTION:
Mapping XS c83b4d18
END DESCRIPTION:
XS GIS Cut Line= 3
      1632544.68      6933130.95      1632412.74      6933405.24
      1632346.77      6933702.13
#Sta/Elev= 30
  4701.0 1646.56  4730.2 1645.61  4758.3 1645.28  4775.4 1644.43  4781.0 1643.04
  4786.5 1643.22  4819.8 1641.17  4826.2 1640.22  4842.0 1639.11  4848.9 1637.74
  4854.4 1637.65  4871.5 1635.86  4922.3 1633.60  4952.9 1633.44  4962.0 1633.12
  5002.0 1630.98  5002.3 1630.48  5006.0 1630.48  5006.2 1630.98  5028.7 1631.23
  5069.7 1634.76  5107.9 1637.13  5113.0 1637.10  5131.1 1638.45  5156.5 1638.98
  5192.6 1640.29  5248.7 1642.91  5254.1 1643.58  5264.3 1643.54  5309.5 1644.70
#Mann=3,-1,0
  4701.0    0.05       0  5002.0    0.05       0  5006.2    0.05       0
Bank Sta=5002,5006.2
Exp/Cntr=0.3,0.1

Type RM Length L Ch R = 1,5616,183,183,183
BEGIN DESCRIPTION:
Deadman 09 12.0
END DESCRIPTION:
XS GIS Cut Line= 3
      1632155.00      6933188.05      1632155.00      6933338.00
      1632304.98      6933687.96
#Sta/Elev= 30
  4849.7 1643.93  4869.7 1643.06  4889.7 1640.19  4899.7 1637.89  4909.7 1635.98
  4929.7 1633.60  4979.7 1629.07  4989.7 1628.27  4995.0 1628.27  4995.3 1627.77
  4999.0 1627.77  4999.3 1628.27  5014.2 1628.92  5021.4 1629.93  5061.3 1632.16
  5090.3 1633.12  5130.2 1635.50  5152.0 1636.08  5173.7 1637.30  5206.4 1637.73
  5213.6 1638.21  5271.6 1640.24  5282.5 1640.91  5304.3 1641.54  5313.3 1642.17
  5318.8 1642.12  5347.8 1643.06  5358.7 1643.16  5371.4 1643.75  5380.4 1643.83
#Mann=3,-1,0
  4849.7    0.05       0  4995.0    0.05       0  4999.3    0.05       0
Bank Sta=4995,4999.3
Exp/Cntr=0.3,0.1

Type RM Length L Ch R = 1,5433,283,283,283
BEGIN DESCRIPTION:
Mapping XS 74c01476
END DESCRIPTION:
XS GIS Cut Line= 3
      1632030.77      6933139.65      1631980.45      6933224.69
      1631952.67      6933641.35
#Sta/Elev= 30
  4787.0 1643.68  4789.7 1642.70  4811.1 1641.46  4842.4 1640.38  4854.8 1639.43
  4869.6 1638.85  4884.8 1637.47  4893.3 1637.39  4899.2 1636.43  4909.2 1635.38
  4979.3 1629.97  4997.2 1627.18  4997.5 1626.68  5001.2 1626.68  5001.5 1627.18
  5029.4 1627.41  5038.7 1627.88  5043.7 1627.76  5069.5 1628.57  5089.6 1630.59
  5129.7 1633.35  5139.7 1634.48  5149.7 1634.66  5189.0 1637.29  5194.0 1637.12
  5199.8 1637.90  5219.9 1639.12  5239.9 1640.74  5259.9 1641.08  5303.4 1642.88
#Mann=3,-1,0
  4787.0    0.05       0  4997.2    0.05       0  5001.5    0.05       0
Bank Sta=4997.2,5001.5
Exp/Cntr=0.3,0.1

Type RM Length L Ch R = 1,5150,252,252,252
BEGIN DESCRIPTION:
Deadman 09 11.0
END DESCRIPTION:
XS GIS Cut Line= 3
      1632005.01      6933087.99      1631705.00      6933388.00
      1631655.01      6933587.96
#Sta/Elev= 30
  4575.4 1641.96  4632.0 1639.96  4688.6 1638.52  4745.1 1636.11  4787.5 1633.33
  4830.0 1631.39  4858.3 1630.28  4900.7 1629.06  4929.0 1627.44  4971.4 1625.75
  4994.0 1625.54  4994.3 1625.04  4998.0 1625.04  4998.3 1625.54  5010.0 1625.91
  5017.7 1626.61  5022.9 1626.55  5051.2 1629.14  5059.0 1630.55  5071.8 1631.33
  5100.2 1634.83  5105.3 1634.93  5123.4 1637.90  5141.4 1639.18  5146.6 1639.22
  5154.3 1640.13  5174.9 1641.75  5182.6 1641.64  5187.8 1642.46  5205.8 1642.94
#Mann=3,-1,0
  4575.4    0.05       0  4994.0    0.05       0  4998.3    0.05       0
Bank Sta=4994,4998.3
Exp/Cntr=0.3,0.1

Type RM Length L Ch R = 1,4898,214,214,214
BEGIN DESCRIPTION:
Mapping XS 30e8d4e7
END DESCRIPTION:
XS GIS Cut Line= 2
      1631572.45      6933044.17      1631419.67      6933476.47
#Sta/Elev= 30
  4718.0 1637.06  4726.4 1637.21  4732.7 1636.45  4743.3 1636.07  4782.9 1633.29
  4788.2 1633.50  4789.9 1633.26  4796.3 1632.34  4819.1 1631.44  4844.7 1629.42
  4875.6 1628.68  4881.2 1627.87  4891.8 1627.22  4913.0 1626.23  4932.2 1625.78
  4955.4 1624.44  4976.6 1624.13  4996.9 1622.83  4997.2 1622.33  5001.3 1622.33
  5001.6 1622.83  5019.0 1623.75  5050.5 1628.10  5072.1 1630.42  5081.4 1631.05
  5112.3 1636.64  5135.7 1638.36  5143.3 1639.45  5148.6 1639.41  5176.5 1641.07
#Mann=4,-1,0
  4718.0    0.12       0  4789.9    0.05       0  4996.9    0.05       0
  5001.6    0.05       0
Bank Sta=4996.9,5001.6
Exp/Cntr=0.3,0.1

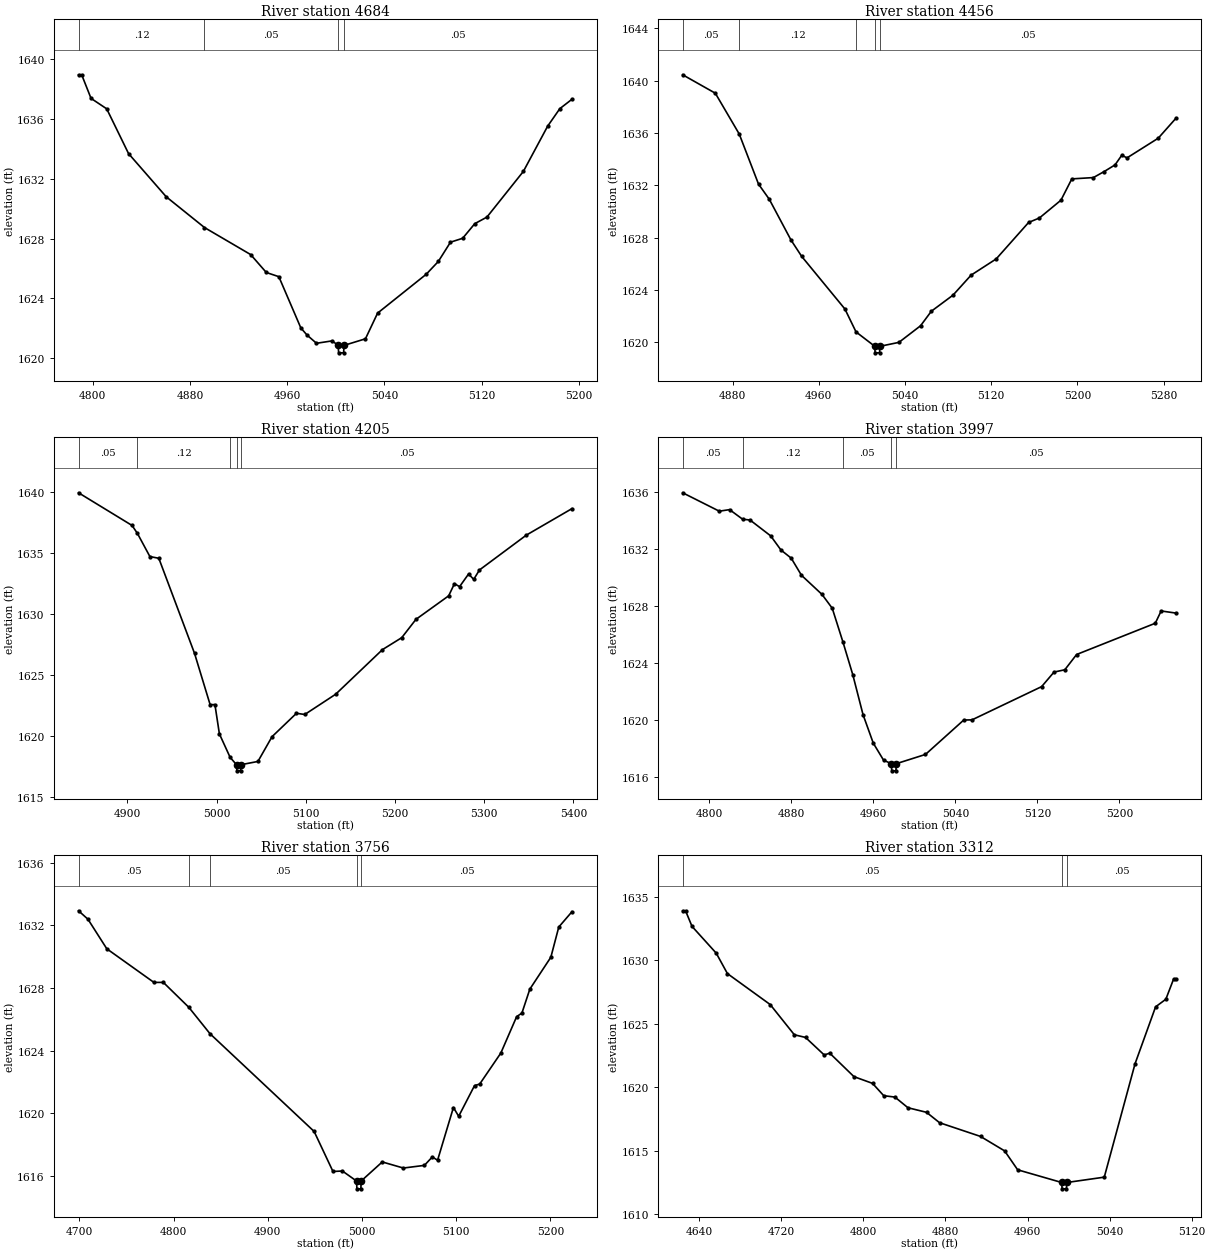
Type RM Length L Ch R = 1,4684,228,228,228
BEGIN DESCRIPTION:
Deadman 09 10.0
END DESCRIPTION:
XS GIS Cut Line= 3
      1631355.00      6932987.99      1631305.00      6933188.00
      1631305.00      6933388.03
#Sta/Elev= 30
  4788.2 1638.97  4790.8 1638.97  4798.5 1637.39  4811.4 1636.69  4829.4 1633.69
  4860.4 1630.80  4891.9 1628.74  4929.9 1626.93  4942.8 1625.73  4953.1 1625.45
  4971.2 1622.02  4976.3 1621.54  4984.1 1620.99  4996.9 1621.15  5002.0 1620.85
  5002.3 1620.35  5006.4 1620.35  5006.8 1620.85  5024.4 1621.29  5034.4 1623.01
  5074.4 1625.61  5084.4 1626.47  5094.4 1627.76  5104.4 1628.02  5114.4 1629.00
  5124.4 1629.44  5154.4 1632.50  5174.4 1635.53  5184.4 1636.70  5194.4 1637.33
#Mann=4,-1,0
  4788.2    0.12       0  4891.9    0.05       0  5002.0    0.05       0
  5006.8    0.05       0
Bank Sta=5002,5006.8
Exp/Cntr=0.3,0.1

Type RM Length L Ch R = 1,4456,251,251,251
BEGIN DESCRIPTION:
Mapping XS 88686401
END DESCRIPTION:
XS GIS Cut Line= 2
      1631119.34      6932927.77      1631086.46      6933384.59
#Sta/Elev= 30
  4833.6 1640.46  4863.9 1639.05  4886.1 1635.93  4904.0 1632.10  4914.0 1630.94
  4934.1 1627.83  4944.1 1626.57  4984.2 1622.55  4994.5 1620.80  5011.9 1619.70
  5012.2 1619.20  5016.3 1619.20  5016.7 1619.70  5034.3 1620.00  5054.4 1621.27
  5064.4 1622.38  5084.5 1623.61  5101.3 1625.14  5124.6 1626.38  5154.7 1629.17
  5164.7 1629.51  5184.7 1630.87  5194.8 1632.50  5214.8 1632.60  5224.8 1633.06
  5234.9 1633.57  5241.1 1634.30  5246.1 1634.11  5275.0 1635.61  5291.6 1637.15
#Mann=5,-1,0
  4833.6    0.05       0  4886.1    0.12       0  4994.5    0.05       0
  5011.9    0.05       0  5016.7    0.05       0
Bank Sta=5011.9,5016.7
Exp/Cntr=0.3,0.1

Type RM Length L Ch R = 1,4205,208,208,208
BEGIN DESCRIPTION:
Deadman 09 9.0
END DESCRIPTION:
XS GIS Cut Line= 3
      1630855.00      6932938.01      1630855.00      6933088.00
      1631055.00      6933438.00
#Sta/Elev= 30
  4845.2 1639.94  4905.2 1637.26  4911.2 1636.61  4925.2 1634.71  4935.2 1634.57
  4975.2 1626.78  4992.7 1622.57  4998.1 1622.57  5003.1 1620.17  5015.1 1618.25
  5022.3 1617.64  5022.7 1617.14  5026.8 1617.14  5027.1 1617.64  5046.3 1617.91
  5062.1 1619.94  5089.5 1621.86  5098.8 1621.76  5133.4 1623.42  5185.9 1627.08
  5207.5 1628.06  5223.4 1629.56  5260.1 1631.49  5266.6 1632.49  5272.3 1632.24
  5282.4 1633.28  5288.2 1632.84  5294.6 1633.61  5347.2 1636.47  5398.3 1638.64
#Mann=5,-1,0
  4845.2    0.05       0  4911.2    0.12       0  5015.1    0.05       0
  5022.3    0.07       0  5027.1    0.05       0
Bank Sta=5022.3,5027.1
Exp/Cntr=0.3,0.1

Type RM Length L Ch R = 1,3997,241,241,241
BEGIN DESCRIPTION:
Mapping XS 1fcf4f9a
END DESCRIPTION:
XS GIS Cut Line= 3
      1630671.42      6932962.31      1630680.10      6933191.27
      1630797.90      6933413.90
#Sta/Elev= 30
  4774.2 1635.93  4809.9 1634.64  4819.9 1634.75  4832.6 1634.08  4839.9 1634.02
  4860.0 1632.91  4870.0 1631.92  4880.0 1631.35  4890.0 1630.15  4910.0 1628.81
  4920.0 1627.84  4930.5 1625.46  4940.0 1623.19  4950.0 1620.39  4960.0 1618.39
  4970.0 1617.20  4977.6 1616.95  4978.0 1616.45  4982.1 1616.45  4982.4 1616.95
  5010.9 1617.60  5048.2 1620.01  5056.2 1620.02  5124.1 1622.35  5136.2 1623.37
  5146.7 1623.53  5158.2 1624.60  5234.9 1626.79  5240.6 1627.65  5255.2 1627.50
#Mann=5,-1,0
  4774.2    0.05       0  4832.6    0.12       0  4930.5    0.05       0
  4977.6    0.03       0  4982.4    0.05       0
Bank Sta=4977.6,4982.4
Exp/Cntr=0.3,0.1

Type RM Length L Ch R = 1,3756,444,444,444
BEGIN DESCRIPTION:
Deadman 09 8.0
END DESCRIPTION:
XS GIS Cut Line= 3
      1630455.00      6932938.03      1630455.00      6933238.00
      1630354.99      6933438.02
#Sta/Elev= 30
  4699.2 1632.94  4709.2 1632.40  4729.2 1630.51  4779.2 1628.36  4789.2 1628.36
  4816.2 1626.77  4838.7 1625.08  4949.2 1618.83  4969.2 1616.27  4979.2 1616.30
  4994.2 1615.66  4994.6 1615.16  4998.8 1615.16  4999.1 1615.66  5021.5 1616.88
  5043.9 1616.49  5066.2 1616.66  5074.6 1617.20  5080.2 1616.99  5097.0 1620.36
  5102.6 1619.80  5119.4 1621.76  5124.9 1621.86  5147.3 1623.84  5164.1 1626.17
  5169.7 1626.40  5178.1 1627.93  5200.4 1629.97  5208.8 1631.90  5222.8 1632.88
#Mann=5,-1,0
  4699.2    0.05       0  4816.2    0.12       0  4838.7    0.05       0
  4994.2    0.05       0  4999.1    0.05       0
Bank Sta=4994.2,4999.1
Exp/Cntr=0.3,0.1

Type RM Length L Ch R = 1,3312,215,215,215
BEGIN DESCRIPTION:
Deadman 09 7.0
END DESCRIPTION:
XS GIS Cut Line= 3
      1630205.02      6932837.96      1630055.00      6933188.00
      1630055.00      6933287.97
#Sta/Elev= 30
  4624.0 1633.91  4626.8 1633.91  4633.1 1632.68  4656.7 1630.57  4667.6 1628.96
  4709.3 1626.52  4732.8 1624.14  4743.7 1623.93  4761.9 1622.55  4767.3 1622.69
  4790.9 1620.84  4809.0 1620.31  4819.9 1619.34  4830.8 1619.23  4843.5 1618.39
  4861.6 1618.03  4874.3 1617.21  4914.2 1616.13  4937.7 1614.99  4950.4 1613.50
  4993.3 1612.50  4993.7 1612.00  4997.9 1612.00  4998.3 1612.50  5034.8 1612.92
  5064.8 1621.86  5084.8 1626.34  5094.8 1626.94  5102.3 1628.52  5104.8 1628.52
#Mann=3,-1,0
  4624.0    0.05       0  4993.3    0.03       0  4998.3    0.05       0
Bank Sta=4993.3,4998.3
Exp/Cntr=0.3,0.1

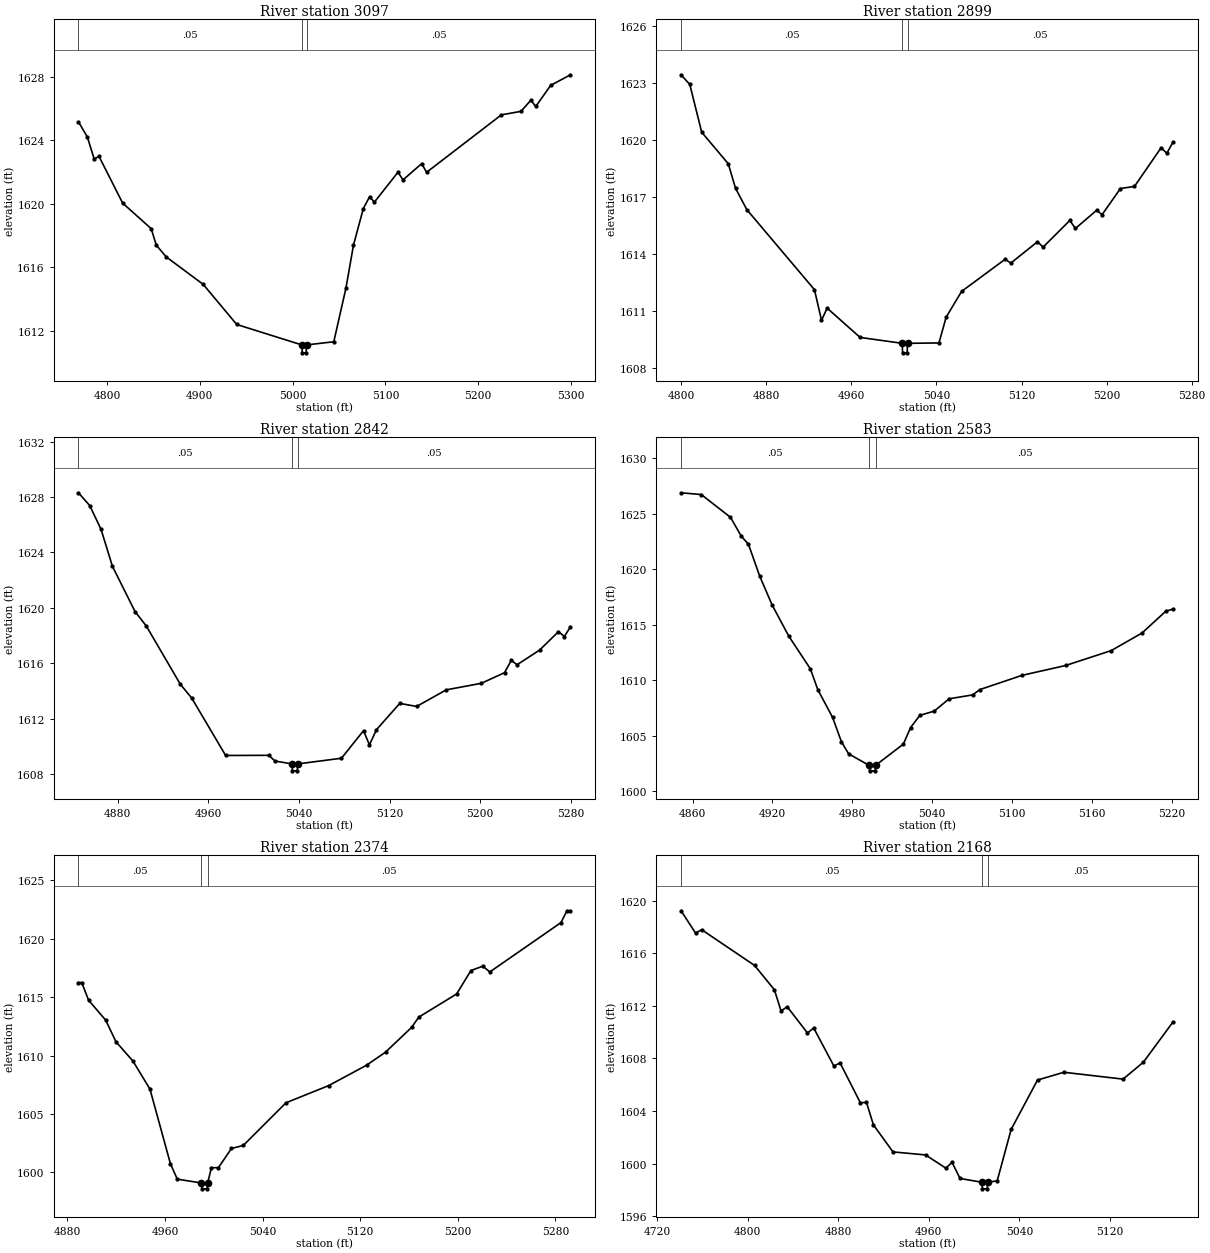
Type RM Length L Ch R = 1,3097,198,198,198
BEGIN DESCRIPTION:
Mapping XS 1a5ae02f
END DESCRIPTION:
XS GIS Cut Line= 2
      1629956.37      6932868.98      1629777.32      6933368.14
#Sta/Elev= 30
  4769.2 1625.18  4778.8 1624.22  4786.1 1622.84  4791.4 1622.99  4816.8 1620.05
  4847.6 1618.43  4853.1 1617.39  4863.8 1616.65  4903.7 1614.91  4939.8 1612.38
  5010.0 1611.09  5010.4 1610.59  5014.6 1610.59  5015.0 1611.09  5044.4 1611.29
  5057.5 1614.68  5065.6 1617.39  5076.2 1619.70  5082.9 1620.44  5088.2 1620.11
  5113.6 1622.00  5119.0 1621.51  5139.1 1622.54  5144.4 1621.99  5225.0 1625.62
  5246.2 1625.84  5256.7 1626.54  5262.1 1626.15  5278.1 1627.48  5299.5 1628.15
#Mann=3,-1,0
  4769.2    0.05       0  5010.0    0.03       0  5015.0    0.05       0
Bank Sta=5010,5015
Exp/Cntr=0.3,0.1

Type RM Length L Ch R = 1,2899,57,57,57
BEGIN DESCRIPTION:
Mapping XS 8bbb0129
END DESCRIPTION:
XS GIS Cut Line= 3
      1629764.29      6932839.73      1629703.54      6933012.23
      1629606.42      6933274.44
#Sta/Elev= 30
  4800.0 1623.44  4808.2 1622.93  4819.4 1620.42  4844.4 1618.76  4851.2 1617.47
  4861.8 1616.35  4925.4 1612.14  4932.0 1610.53  4937.3 1611.17  4968.3 1609.63
  5007.9 1609.32  5008.2 1608.82  5012.5 1608.82  5012.9 1609.32  5042.4 1609.34
  5049.2 1610.70  5063.7 1612.05  5104.6 1613.74  5110.0 1613.54  5135.0 1614.66
  5140.3 1614.38  5165.4 1615.78  5170.7 1615.36  5190.5 1616.31  5195.8 1616.09
  5213.0 1617.46  5226.2 1617.57  5251.3 1619.61  5256.6 1619.31  5262.5 1619.91
#Mann=3,-1,0
  4800.0    0.05       0  5007.9    0.03       0  5012.9    0.05       0
Bank Sta=5007.9,5012.9
Exp/Cntr=0.3,0.1

Type RM Length L Ch R = 1,2842,259,259,259
BEGIN DESCRIPTION:
Deadman 09 6.0
END DESCRIPTION:
XS GIS Cut Line= 3
      1629655.00      6932838.00      1629655.00      6932988.00
      1629587.82      6933264.56
#Sta/Elev= 30
  4845.2 1628.31  4855.2 1627.38  4865.2 1625.66  4875.2 1623.00  4895.2 1619.73
  4905.2 1618.68  4935.2 1614.48  4945.2 1613.49  4975.2 1609.34  5013.5 1609.35
  5018.7 1608.94  5033.9 1608.73  5034.2 1608.23  5038.5 1608.23  5038.9 1608.73
  5077.5 1609.14  5097.0 1611.13  5102.2 1610.10  5108.4 1611.20  5129.0 1613.10
  5143.9 1612.88  5170.1 1614.08  5201.0 1614.55  5221.6 1615.32  5227.5 1616.21
  5232.6 1615.89  5252.5 1616.95  5269.2 1618.28  5274.4 1617.93  5279.8 1618.64
#Mann=3,-1,0
  4845.2    0.05       0  5033.9    0.05       0  5038.9    0.05       0
Bank Sta=5033.9,5038.9
Exp/Cntr=0.3,0.1

Type RM Length L Ch R = 1,2583,209,209,209
BEGIN DESCRIPTION:
Mapping XS 5b201c3a
END DESCRIPTION:
XS GIS Cut Line= 2
      1629360.66      6932934.11      1629510.59      6933271.72
#Sta/Elev= 30
  4851.4 1626.90  4866.6 1626.74  4888.5 1624.69  4896.5 1623.01  4902.0 1622.26
  4910.4 1619.40  4919.8 1616.78  4932.2 1614.00  4948.5 1611.03  4954.1 1609.15
  4965.1 1606.68  4971.8 1604.47  4977.2 1603.38  4992.5 1602.35  4992.9 1601.85
  4997.2 1601.85  4997.5 1602.35  5018.3 1604.26  5023.7 1605.75  5030.7 1606.85
  5041.5 1607.23  5052.6 1608.34  5070.3 1608.69  5075.7 1609.17  5107.3 1610.45
  5140.1 1611.34  5174.3 1612.68  5197.5 1614.27  5215.3 1616.23  5220.8 1616.43
#Mann=3,-1,0
  4851.4    0.05       0  4992.5    0.05       0  4997.5    0.05       0
Bank Sta=4992.5,4997.5
Exp/Cntr=0.3,0.1

Type RM Length L Ch R = 1,2374,206,206,206
BEGIN DESCRIPTION:
Deadman 09 5.0
END DESCRIPTION:
XS GIS Cut Line= 3
      1629205.02      6933088.04      1629255.00      6933188.00
      1629405.00      6933438.00
#Sta/Elev= 30
  4889.0 1616.24  4891.7 1616.24  4897.3 1614.73  4911.3 1613.03  4919.7 1611.19
  4933.7 1609.52  4947.6 1607.13  4964.4 1600.74  4970.0 1599.43  4989.8 1599.10
  4990.2 1598.60  4994.5 1598.60  4994.9 1599.10  4998.0 1600.41  5003.7 1600.41
  5014.4 1602.05  5024.1 1602.31  5059.1 1605.96  5094.1 1607.43  5125.1 1609.17
  5140.7 1610.29  5162.1 1612.41  5167.9 1613.28  5199.0 1615.27  5210.7 1617.27
  5220.4 1617.64  5226.2 1617.15  5284.5 1621.37  5289.4 1622.38  5292.3 1622.38
#Mann=3,-1,0
  4889.0    0.05       0  4989.8    0.05       0  4994.9    0.05       0
Bank Sta=4989.8,4994.9
Exp/Cntr=0.3,0.1

Type RM Length L Ch R = 1,2168,249,249,249
BEGIN DESCRIPTION:
Mapping XS f5363876
END DESCRIPTION:
XS GIS Cut Line= 2
      1628984.31      6933052.56      1629159.26      6933450.17
#Sta/Elev= 30
  4741.3 1619.24  4754.1 1617.54  4759.5 1617.80  4806.2 1615.08  4823.7 1613.23
  4829.6 1611.61  4835.0 1611.94  4852.9 1609.94  4858.4 1610.32  4876.2 1607.43
  4881.7 1607.66  4899.6 1604.63  4905.0 1604.66  4911.1 1602.95  4928.4 1600.89
  4957.2 1600.66  4975.1 1599.65  4980.5 1600.10  4987.6 1598.87  5006.9 1598.58
  5007.3 1598.08  5011.6 1598.08  5012.0 1598.58  5020.4 1598.69  5032.7 1602.60
  5056.0 1606.36  5079.3 1606.95  5131.5 1606.43  5149.4 1607.71  5175.7 1610.79
#Mann=3,-1,0
  4741.3    0.05       0  5006.9    0.05       0  5012.0    0.05       0
Bank Sta=5006.9,5012
Exp/Cntr=0.3,0.1

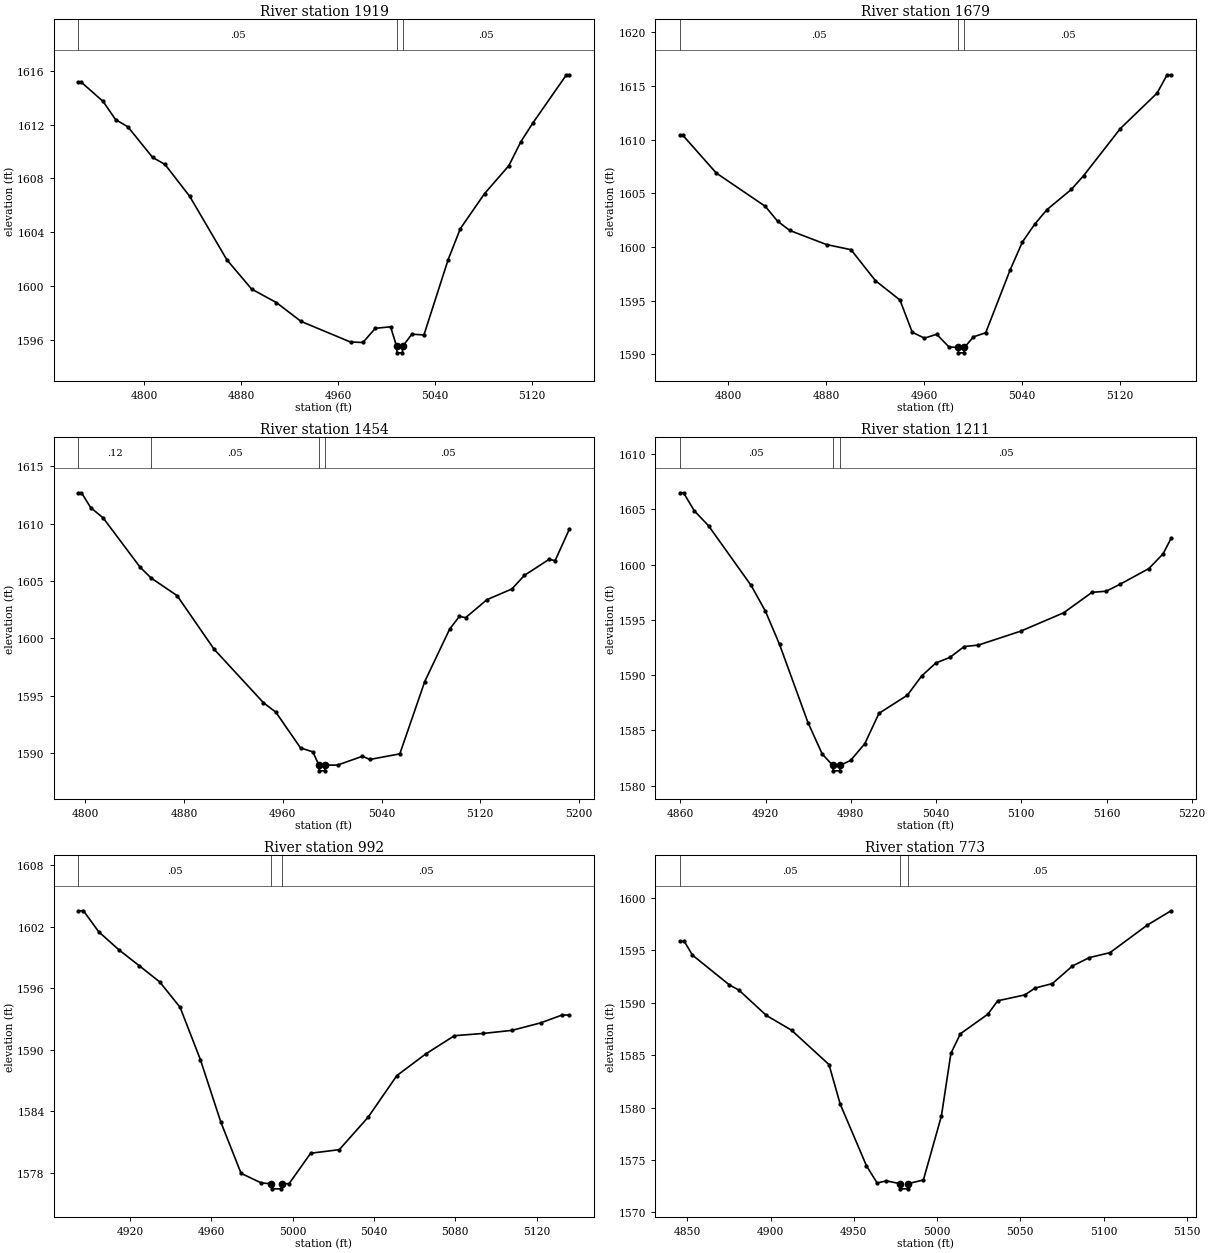
Type RM Length L Ch R = 1,1919,240,240,240
BEGIN DESCRIPTION:
Deadman 09 4.0
END DESCRIPTION:
XS GIS Cut Line= 3
      1628905.00      6933088.00      1628855.00      6933338.00
      1628855.00      6933487.95
#Sta/Elev= 30
  4745.9 1615.13  4748.4 1615.13  4766.3 1613.71  4776.5 1612.37  4786.7 1611.83
  4807.1 1609.56  4817.3 1609.04  4837.7 1606.67  4868.3 1601.97  4888.7 1599.80
  4909.1 1598.80  4929.5 1597.40  4970.3 1595.87  4980.5 1595.84  4990.7 1596.89
  5003.3 1597.00  5008.2 1595.57  5008.6 1595.07  5013.0 1595.07  5013.4 1595.57
  5020.8 1596.45  5030.8 1596.40  5050.8 1601.99  5060.8 1604.28  5080.8 1606.88
  5100.8 1608.95  5110.8 1610.74  5120.8 1612.14  5148.3 1615.69  5150.8 1615.69
#Mann=3,-1,0
  4745.9    0.05       0  5008.2    0.05       0  5013.4    0.05       0
Bank Sta=5008.2,5013.4
Exp/Cntr=0.3,0.1

Type RM Length L Ch R = 1,1679,225,225,225
BEGIN DESCRIPTION:
Mapping XS a7b93c62
END DESCRIPTION:
XS GIS Cut Line= 2
      1628618.69      6933098.36      1628612.61      6933499.41
#Sta/Elev= 30
  4760.5 1610.42  4762.8 1610.42  4790.1 1606.90  4830.2 1603.79  4840.2 1602.41
  4850.2 1601.54  4880.2 1600.23  4900.2 1599.75  4920.2 1596.86  4940.2 1595.06
  4950.2 1592.06  4960.2 1591.51  4970.2 1591.87  4980.2 1590.69  4987.6 1590.64
  4988.0 1590.14  4992.4 1590.14  4992.8 1590.64  5000.2 1591.63  5010.2 1592.01
  5030.2 1597.87  5040.2 1600.47  5050.2 1602.12  5060.2 1603.48  5080.2 1605.37
  5090.2 1606.65  5120.2 1611.04  5150.2 1614.34  5158.4 1616.05  5161.6 1616.05
#Mann=3,-1,0
  4760.5    0.05       0  4987.6    0.05       0  4992.8    0.05       0
Bank Sta=4987.6,4992.8
Exp/Cntr=0.3,0.1

Type RM Length L Ch R = 1,1454,243,243,243
BEGIN DESCRIPTION:
Deadman 09 3.0
END DESCRIPTION:
XS GIS Cut Line= 3
      1628405.00      6933088.05      1628405.00      6933288.00
      1628378.41      6933484.25
#Sta/Elev= 30
  4794.3 1612.69  4796.8 1612.69  4804.3 1611.39  4814.3 1610.51  4844.3 1606.21
  4853.2 1605.27  4874.3 1603.73  4904.3 1599.06  4944.3 1594.40  4954.3 1593.58
  4974.3 1590.47  4984.3 1590.12  4989.2 1588.97  4989.6 1588.47  4994.0 1588.47
  4994.4 1588.97  5004.3 1588.97  5024.5 1589.74  5030.5 1589.46  5054.8 1589.95
  5075.0 1596.25  5095.2 1600.82  5103.1 1601.93  5108.1 1601.81  5125.4 1603.38
  5145.6 1604.31  5155.7 1605.49  5175.6 1606.88  5180.7 1606.79  5192.3 1609.55
#Mann=4,-1,0
  4794.3    0.12       0  4853.2    0.05       0  4989.2    0.05       0
  4994.4    0.05       0
Bank Sta=4989.2,4994.4
Exp/Cntr=0.3,0.1

Type RM Length L Ch R = 1,1211,219,219,219
BEGIN DESCRIPTION:
Mapping XS 658333cd
END DESCRIPTION:
XS GIS Cut Line= 2
      1628160.35      6933147.90      1628164.68      6933493.57
#Sta/Elev= 30
  4859.7 1606.49  4862.2 1606.49  4869.8 1604.86  4879.8 1603.51  4909.8 1598.11
  4919.8 1595.80  4929.8 1592.78  4949.8 1585.72  4959.8 1582.88  4967.2 1581.85
  4967.6 1581.35  4972.1 1581.35  4972.5 1581.85  4979.8 1582.29  4989.8 1583.80
  4999.8 1586.55  5019.8 1588.19  5029.8 1589.92  5039.8 1591.10  5049.8 1591.61
  5059.8 1592.59  5069.8 1592.72  5099.8 1593.99  5129.8 1595.64  5149.8 1597.49
  5159.8 1597.59  5169.8 1598.24  5189.8 1599.64  5199.8 1600.97  5205.4 1602.36
#Mann=3,-1,0
  4859.7    0.05       0  4967.2    0.05       0  4972.5    0.05       0
Bank Sta=4967.2,4972.5
Exp/Cntr=0.3,0.1

Type RM Length L Ch R = 1,992,219,219,219
BEGIN DESCRIPTION:
Deadman 09 2.0
END DESCRIPTION:
XS GIS Cut Line= 3
      1627955.00      6933237.95      1627955.00      6933338.00
      1628055.02      6933438.02
#Sta/Elev= 27
  4894.7 1603.55  4897.2 1603.55  4904.7 1601.50  4914.7 1599.73  4924.7 1598.18
  4934.7 1596.61  4944.7 1594.14  4954.7 1589.03  4964.7 1582.97  4974.7 1577.95
  4984.7 1577.01  4989.6 1576.94  4990.0 1576.44  4994.5 1576.44  4994.9 1576.94
  4998.3 1576.94  5008.9 1579.91  5023.0 1580.26  5037.2 1583.43  5051.3 1587.48
  5065.5 1589.59  5079.6 1591.37  5093.7 1591.59  5107.9 1591.89  5122.0 1592.62
  5132.6 1593.39  5136.2 1593.39
#Mann=3,-1,0
  4894.7    0.05       0  4989.6    0.05       0  4994.9    0.05       0
Bank Sta=4989.6,4994.9
Exp/Cntr=0.3,0.1

Type RM Length L Ch R = 1,773,211,211,211
BEGIN DESCRIPTION:
Mapping XS 6f2bc5d4
END DESCRIPTION:
XS GIS Cut Line= 2
      1627725.47      6933348.40      1627860.45      6933610.59
#Sta/Elev= 30
  4845.6 1595.86  4848.2 1595.86  4853.1 1594.55  4875.3 1591.70  4880.9 1591.22
  4897.5 1588.79  4912.6 1587.38  4935.1 1584.10  4941.8 1580.34  4957.6 1574.44
  4964.0 1572.80  4969.6 1573.00  4977.5 1572.74  4977.9 1572.24  4982.4 1572.24
  4982.8 1572.74  4991.8 1573.09  5002.6 1579.19  5008.3 1585.17  5014.0 1587.04
  5030.5 1588.91  5036.4 1590.19  5052.7 1590.75  5058.8 1591.40  5069.2 1591.83
  5081.3 1593.51  5091.4 1594.31  5103.8 1594.78  5126.3 1597.42  5140.5 1598.78
#Mann=3,-1,0
  4845.6    0.05       0  4977.5    0.05       0  4982.8    0.05       0
Bank Sta=4977.5,4982.8
Exp/Cntr=0.3,0.1

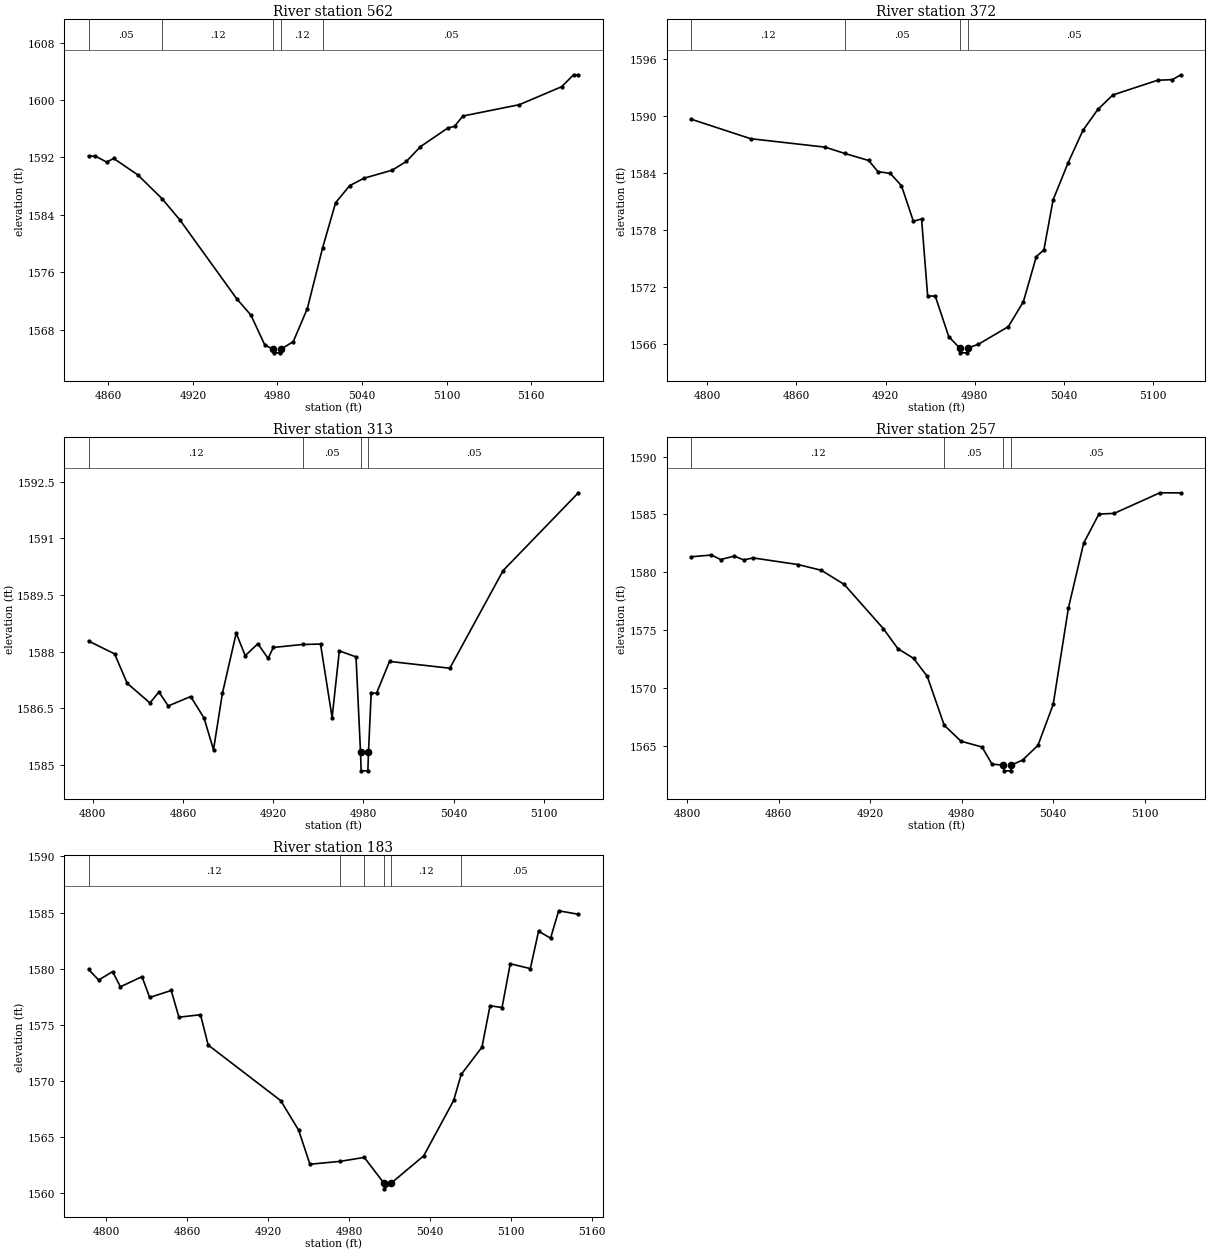
Type RM Length L Ch R = 1,562,190,190,190
BEGIN DESCRIPTION:
Mapping XS 28018269
END DESCRIPTION:
XS GIS Cut Line= 2
      1627588.71      6933383.20      1627617.28      6933729.73
#Sta/Elev= 30
  4845.9 1592.17  4850.8 1592.17  4858.7 1591.34  4863.7 1591.85  4880.8 1589.56
  4898.2 1586.21  4910.9 1583.23  4951.1 1572.28  4961.1 1570.02  4971.1 1565.81
  4977.1 1565.25  4977.5 1564.75  4982.0 1564.75  4982.4 1565.25  4991.2 1566.31
  5001.2 1570.92  5012.1 1579.43  5021.3 1585.69  5031.3 1588.06  5041.4 1589.09
  5061.4 1590.21  5071.5 1591.43  5081.5 1593.49  5100.8 1596.07  5105.8 1596.34
  5111.6 1597.76  5151.7 1599.34  5181.8 1601.85  5190.2 1603.51  5193.6 1603.51
#Mann=5,-1,0
  4845.9    0.05       0  4898.2    0.12       0  4977.1    0.07       0
  4982.4    0.12       0  5012.1    0.05       0
Bank Sta=4977.1,4982.4
Exp/Cntr=0.3,0.1

Type RM Length L Ch R = 1,372,59,59,59
BEGIN DESCRIPTION:
Mapping XS 09319bbb
END DESCRIPTION:
XS GIS Cut Line= 4
      1627534.49      6933380.96      1627428.26      6933459.35
      1627416.54      6933484.99      1627401.94      6933653.65
#Sta/Elev= 30
  4789.2 1589.69  4829.2 1587.63  4879.3 1586.74  4892.6 1586.07  4908.6 1585.33
  4914.8 1584.16  4923.2 1583.96  4930.7 1582.66  4938.7 1578.91  4944.2 1579.16
  4948.3 1571.02  4953.4 1571.02  4962.5 1566.73  4969.9 1565.52  4970.3 1565.02
  4974.8 1565.02  4975.2 1565.52  4982.5 1565.93  5002.6 1567.79  5012.7 1570.42
  5021.4 1575.18  5026.5 1575.89  5032.7 1581.17  5042.8 1585.09  5052.8 1588.52
  5062.8 1590.72  5072.9 1592.25  5103.0 1593.80  5113.0 1593.87  5118.7 1594.38
#Mann=4,-1,0
  4789.2    0.12       0  4892.6    0.05       0  4969.9    0.05       0
  4975.2    0.05       0
Bank Sta=4969.9,4975.2
Exp/Cntr=0.3,0.1

Type RM Length L Ch R = 1,313,56,56,56
BEGIN DESCRIPTION:
Mapping XS 5d7c903f
END DESCRIPTION:
XS GIS Cut Line= 5
      1627509.55      6933367.79      1627404.08      6933435.90
      1627375.51      6933470.34      1627365.99      6933489.39
      1627356.48      6933623.26
#Sta/Elev= 30
  4797.2 1588.28  4814.5 1587.94  4822.9 1587.16  4838.0 1586.64  4844.0 1586.93
  4850.2 1586.56  4865.1 1586.81  4874.0 1586.24  4880.3 1585.40  4886.2 1586.89
  4895.4 1588.49  4901.4 1587.89  4909.8 1588.21  4916.6 1587.82  4920.1 1588.11
  4939.6 1588.19  4951.5 1588.20  4959.2 1586.25  4964.0 1588.02  4975.1 1587.86
  4978.1 1585.34  4978.5 1584.84  4983.0 1584.84  4983.4 1585.34  4985.2 1586.90
  4988.8 1586.90  4997.4 1587.74  5037.5 1587.56  5073.0 1590.15  5123.0 1592.21
#Mann=4,-1,0
  4797.2    0.12       0  4939.6    0.05       0  4978.1    0.05       0
  4983.4    0.05       0
Bank Sta=4978.1,4983.4
Exp/Cntr=0.3,0.1

Type RM Length L Ch R = 1,257,74,74,74
BEGIN DESCRIPTION:
Mapping XS 61db5cf5
END DESCRIPTION:
XS GIS Cut Line= 4
      1627398.98      6933314.26      1627327.89      6933420.52
      1627311.77      6933481.33      1627316.90      6933611.77
#Sta/Elev= 30
  4802.5 1581.34  4815.8 1581.49  4821.8 1581.10  4830.8 1581.40  4836.9 1581.07
  4843.1 1581.24  4872.9 1580.66  4887.9 1580.17  4902.9 1578.95  4928.5 1575.14
  4938.1 1573.40  4948.4 1572.56  4957.4 1571.00  4968.5 1566.78  4979.5 1565.40
  4993.3 1564.90  4999.9 1563.41  5007.3 1563.34  5007.7 1562.84  5012.2 1562.84
  5012.6 1563.34  5019.9 1563.77  5030.0 1565.04  5040.0 1568.58  5050.0 1576.92
  5060.0 1582.52  5070.0 1585.03  5080.0 1585.09  5110.0 1586.87  5123.8 1586.86
#Mann=4,-1,0
  4802.5    0.12       0  4968.5    0.05       0  5007.3    0.05       0
  5012.6    0.05       0
Bank Sta=5007.3,5012.6
Exp/Cntr=0.3,0.1

Type RM Length L Ch R = 1,183,0,0,0
BEGIN DESCRIPTION:
Deadman 09 1.0
END DESCRIPTION:
XS GIS Cut Line= 3
      1627341.10      6933301.80      1627231.92      6933498.18
      1627309.57      6933612.99
#Sta/Elev= 30
  4786.9 1579.93  4794.4 1578.99  4804.7 1579.74  4810.5 1578.39  4826.5 1579.29
  4832.2 1577.44  4848.2 1578.06  4853.9 1575.68  4869.9 1575.90  4875.6 1573.20
  4929.4 1568.25  4942.7 1565.62  4951.1 1562.58  4973.6 1562.84  4991.4 1563.19
  5006.0 1560.89  5006.4 1560.39  5011.3 1560.89  5035.5 1563.33  5057.7 1568.26
  5063.3 1570.58  5078.7 1573.01  5084.7 1576.70  5093.6 1576.54  5099.7 1580.44
  5114.6 1580.01  5120.7 1583.34  5129.6 1582.72  5135.6 1585.16  5150.2 1584.85
#Mann=6,-1,0
  4786.9    0.12       0  4973.6    0.05       0  4991.4    0.12       0
  5006.0    0.07       0  5011.3    0.12       0  5063.3    0.05       0
Bank Sta=5006,5011.3
Exp/Cntr=0.3,0.1

Chan Stop Cuts=-1