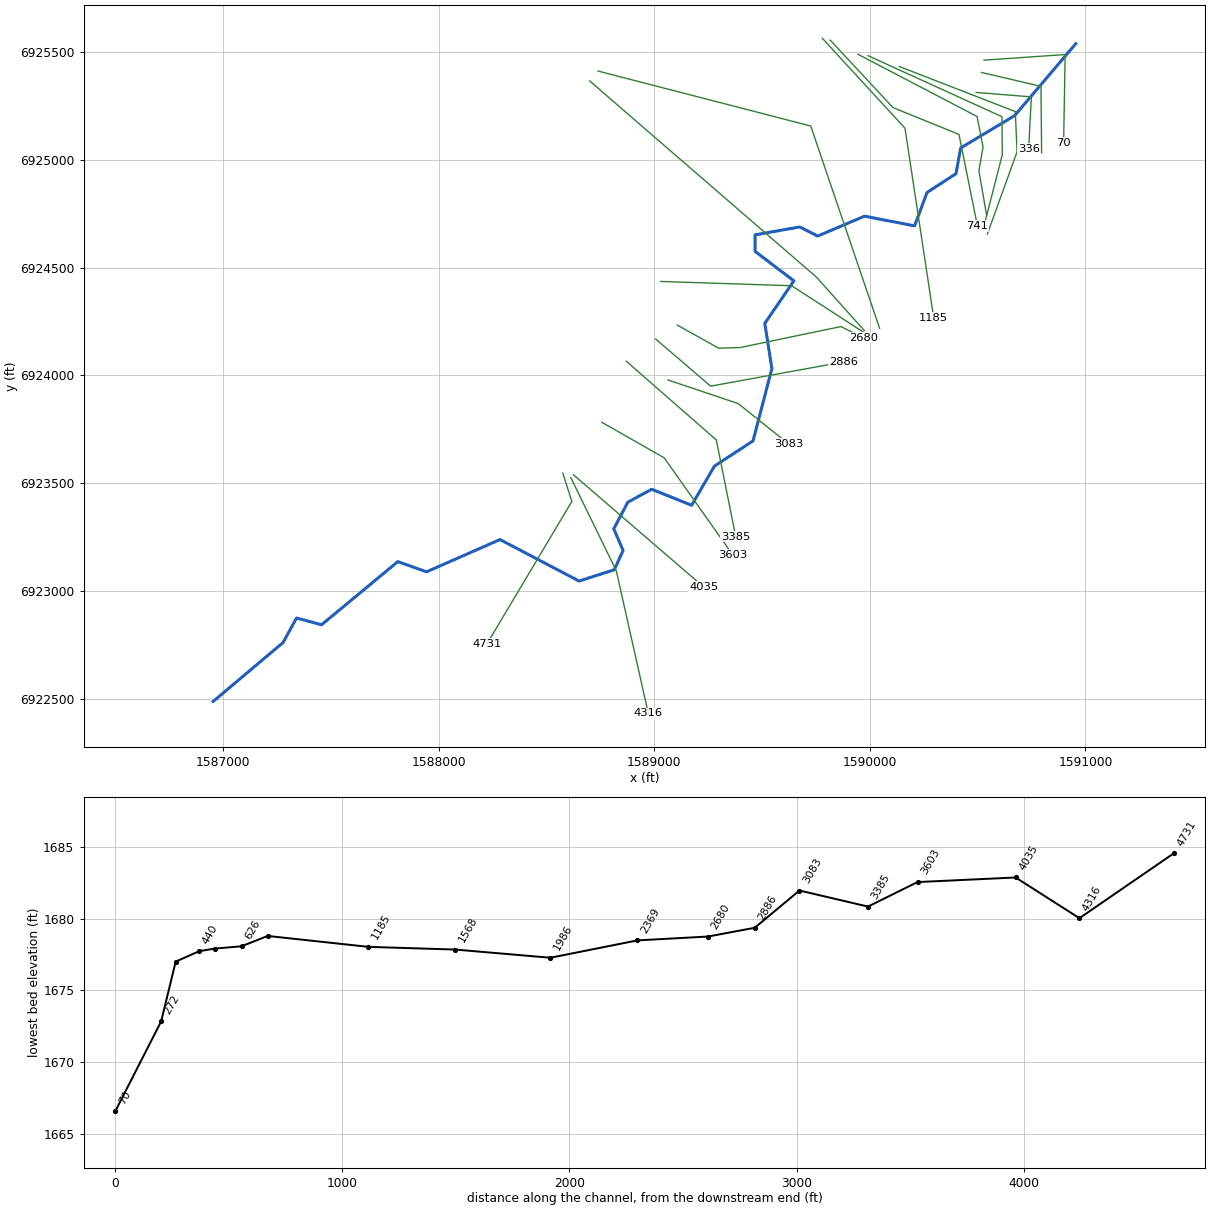
--- Deadman 10.prj (project) ---

Proj Title=Deadman 10 Base Level Engineering
Current Plan=p01
Default Exp/Contr=0.3,0.1
English Units
Geom File=g01
Flow File=f01
Plan File=p01
Y Axis Title=Elevation
X Axis Title(PF)=Main Channel Distance
X Axis Title(XS)=Station
BEGIN DESCRIPTION:
Deadman 10
END DESCRIPTION:
DSS Export Rating Curves= 0
DSS Export Rating Curve Sorted= 0
DSS Export Volume Flow Curves= 0
DXF OffsetX= 0
DXF OffsetY= 0
DXF ScaleX= 1
DXF ScaleY= 10

--- Deadman 10.p01 (plan) ---

Plan Title=Multiple Run
Short Identifier=Multiple
Geom File=g01
Flow File=f01
Subcritical Flow
K Sum by GR= 0
Std Step Tol= 0.01
Critical Tol= 0.01
Num of Std Step Trials= 20
Max Error Tol= 0.3
Flow Tol Ratio= 0.001
Split Flow NTrial= 30
Split Flow Tol= 0.02
Split Flow Ratio= 0.02
Log Output Level= 0
Friction Slope Method= 1
Unsteady Friction Slope Method= 2
Unsteady Bridges Friction Slope Method= 1
Parabolic Critical Depth
Global Vel Dist=  1 , 1 , 1
Global Log Level= 0
CheckData=True
Encroach Param= -1, 0, 0, 0
BEGIN DESCRIPTION:
Multiple Run
END DESCRIPTION:

--- Deadman 10.f01 (steady flow) ---

Flow Title=Multiple
Number of Profiles=7
Profile Names=10-year,25-year,50-year,1pct_min,100-year,1pct_plu,500-year
River Rch & RM= Deadman 10,Reach-1,4731
     135     175     205     119     238     474     325
Boundary for River Rch & Prof#=Deadman 10,Reach-1,1
Up Type=0
Dn Type=3
Dn Slope=0.05
Boundary for River Rch & Prof#=Deadman 10,Reach-1,2
Up Type=0
Dn Type=3
Dn Slope=0.05
Boundary for River Rch & Prof#=Deadman 10,Reach-1,3
Up Type=0
Dn Type=3
Dn Slope=0.05
Boundary for River Rch & Prof#=Deadman 10,Reach-1,4
Up Type=0
Dn Type=3
Dn Slope=0.05
Boundary for River Rch & Prof#=Deadman 10,Reach-1,5
Up Type=0
Dn Type=3
Dn Slope=0.05
Boundary for River Rch & Prof#=Deadman 10,Reach-1,6
Up Type=0
Dn Type=3
Dn Slope=0.05
Boundary for River Rch & Prof#=Deadman 10,Reach-1,7
Up Type=0
Dn Type=3
Dn Slope=0.05

--- Deadman 10.g01 (geometry) ---

Geom Title=Existing Conditions

River Reach=Deadman 10,Reach-1
Reach XY= 30
      1586955.00      6922488.00      1587278.84      6922760.87
      1587341.27      6922874.60      1587457.29      6922843.12
      1587811.11      6923136.20      1587944.31      6923088.75
      1588284.87      6923238.39      1588651.70      6923046.08
      1588815.17      6923098.36      1588855.83      6923187.97
      1588812.53      6923288.01      1588877.85      6923411.83
      1588988.52      6923471.71      1589173.57      6923397.31
      1589279.26      6923578.82      1589458.46      6923695.99
      1589545.84      6924031.00      1589513.07      6924241.31
      1589648.01      6924438.22      1589468.09      6924574.78
      1589467.93      6924651.63      1589675.18      6924688.29
      1589758.30      6924646.08      1589975.18      6924738.28
      1590207.73      6924693.34      1590265.39      6924848.10
      1590399.58      6924935.33      1590421.44      6925054.79
      1590671.68      6925204.64      1590955.00      6925538.00

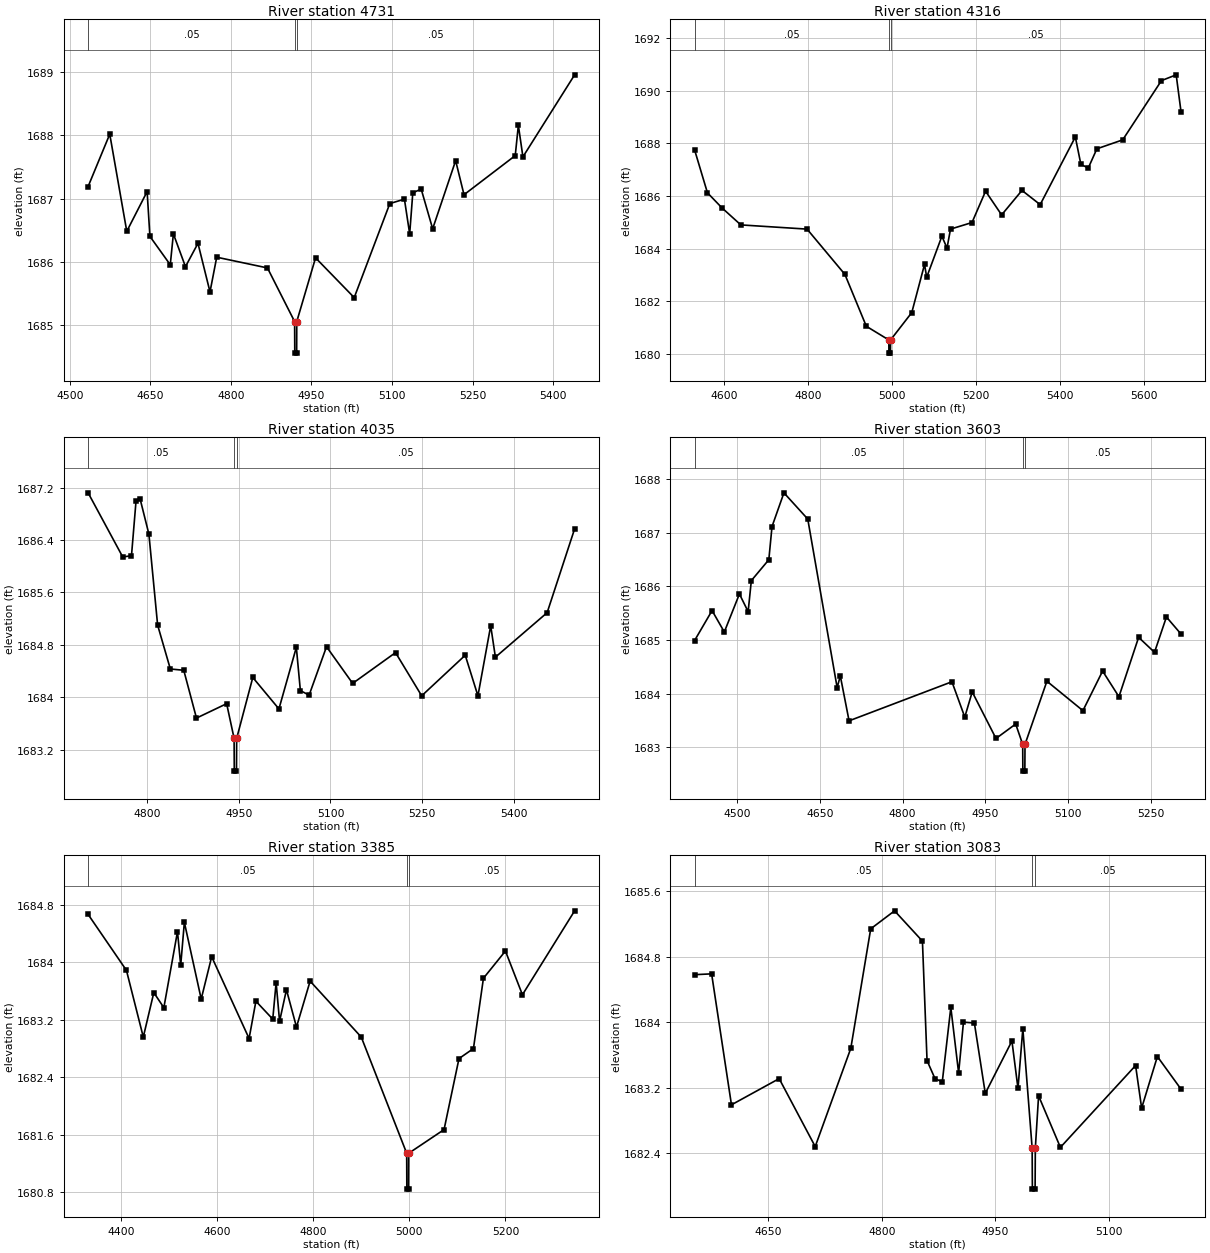
Type RM Length L Ch R = 1,4731,415,415,415
BEGIN DESCRIPTION:
Mapping XS 0e7d80f6
END DESCRIPTION:
XS GIS Cut Line= 3
      1588576.22      6923546.62      1588618.17      6923415.34
      1588225.00      6922755.29
#Sta/Elev= 30
  4534.0 1687.19  4574.3 1688.02  4606.0 1686.48  4643.9 1687.11  4649.1 1686.40
  4687.0 1685.95  4692.8 1686.44  4715.3 1685.92  4738.6 1686.29  4761.0 1685.52
  4773.5 1686.07  4868.0 1685.90  4918.6 1685.05  4918.9 1684.55  4922.4 1684.55
  4922.6 1685.05  4957.6 1686.06  5029.6 1685.43  5095.9 1686.92  5123.1 1686.99
  5132.9 1686.44  5138.7 1687.09  5154.3 1687.15  5175.7 1686.52  5218.5 1687.60
  5234.1 1687.06  5329.5 1687.68  5335.3 1688.16  5343.8 1687.66  5440.1 1688.96
#Mann=3,-1,0
  4534.0    0.05       0  4918.6    0.05       0  4922.6    0.05       0
Bank Sta=4918.6,4922.6
Exp/Cntr=0.3,0.1

Type RM Length L Ch R = 1,4316,281,281,281
BEGIN DESCRIPTION:
Mapping XS 3be655fd
END DESCRIPTION:
XS GIS Cut Line= 3
      1588613.47      6923525.47      1588824.41      6923093.17
      1588972.71      6922432.33
#Sta/Elev= 30
  4529.6 1687.75  4560.2 1686.12  4594.6 1685.55  4639.7 1684.90  4797.4 1684.74
  4887.5 1683.02  4938.5 1681.05  4992.1 1680.53  4992.3 1680.03  4995.9 1680.03
  4996.2 1680.53  5046.7 1681.57  5077.1 1683.40  5082.2 1682.91  5118.4 1684.47
  5130.6 1684.02  5138.9 1684.74  5190.1 1684.99  5222.4 1686.18  5260.6 1685.28
  5309.1 1686.21  5352.4 1685.67  5436.1 1688.24  5449.3 1687.20  5466.9 1687.06
  5487.4 1687.79  5548.9 1688.13  5641.1 1690.38  5676.2 1690.60  5687.9 1689.18
#Mann=3,-1,0
  4529.6    0.05       0  4992.1    0.03       0  4996.2    0.05       0
Bank Sta=4992.1,4996.2
Exp/Cntr=0.3,0.1

Type RM Length L Ch R = 1,4035,432,432,432
BEGIN DESCRIPTION:
Mapping XS 605708fd
END DESCRIPTION:
XS GIS Cut Line= 2
      1588625.59      6923538.81      1589229.08      6923019.00
#Sta/Elev= 30
  4703.2 1687.12  4759.9 1686.14  4774.2 1686.16  4781.6 1686.99  4788.5 1687.02
  4802.7 1686.49  4817.0 1685.10  4837.8 1684.43  4859.8 1684.41  4880.6 1683.68
  4930.0 1683.90  4942.2 1683.37  4942.5 1682.87  4946.1 1682.87  4946.4 1683.37
  4972.8 1684.30  5015.6 1683.82  5044.1 1684.76  5050.7 1684.10  5065.0 1684.03
  5093.5 1684.77  5136.3 1684.21  5206.5 1684.68  5249.3 1684.02  5320.6 1684.64
  5341.4 1684.02  5362.3 1685.09  5370.0 1684.61  5454.7 1685.29  5499.7 1686.57
#Mann=3,-1,0
  4703.2    0.05       0  4942.2    0.03       0  4946.4    0.05       0
Bank Sta=4942.2,4946.4
Exp/Cntr=0.3,0.1

Type RM Length L Ch R = 1,3603,218,218,218
BEGIN DESCRIPTION:
Mapping XS 235a0c7f
END DESCRIPTION:
XS GIS Cut Line= 3
      1588757.47      6923782.18      1589046.51      6923617.38
      1589363.43      6923168.62
#Sta/Elev= 30
  4423.0 1684.99  4454.7 1685.55  4476.9 1685.15  4504.3 1685.86  4520.1 1685.53
  4525.9 1686.11  4557.6 1686.50  4563.4 1687.12  4585.0 1687.75  4628.2 1687.26
  4681.5 1684.11  4687.2 1684.33  4703.1 1683.49  4889.6 1684.22  4912.9 1683.56
  4926.4 1684.03  4969.5 1683.16  5005.2 1683.43  5017.9 1683.05  5018.2 1682.55
  5021.8 1682.55  5022.1 1683.05  5061.8 1684.23  5127.1 1683.68  5162.8 1684.42
  5192.4 1683.94  5228.1 1685.05  5256.9 1684.77  5278.5 1685.43  5305.1 1685.11
#Mann=3,-1,0
  4423.0    0.05       0  5017.9    0.03       0  5022.1    0.05       0
Bank Sta=5017.9,5022.1
Exp/Cntr=0.3,0.1

Type RM Length L Ch R = 1,3385,302,302,302
BEGIN DESCRIPTION:
Mapping XS f703370b
END DESCRIPTION:
XS GIS Cut Line= 3
      1588870.30      6924065.89      1589288.09      6923700.51
      1589378.32      6923251.41
#Sta/Elev= 30
  4330.9 1684.67  4410.7 1683.89  4445.8 1682.96  4467.7 1683.58  4488.6 1683.37
  4517.0 1684.43  4523.7 1683.96  4531.3 1684.56  4566.4 1683.49  4588.2 1684.08
  4666.1 1682.94  4680.3 1683.46  4715.4 1683.21  4722.4 1683.72  4729.6 1683.18
  4743.9 1683.62  4764.8 1683.10  4793.2 1683.74  4899.7 1682.96  4994.3 1681.34
  4994.6 1680.84  4998.2 1680.84  4998.5 1681.34  5072.1 1681.67  5103.2 1682.66
  5133.3 1682.80  5154.1 1683.78  5199.9 1684.16  5235.3 1683.55  5344.0 1684.72
#Mann=3,-1,0
  4330.9    0.05       0  4994.3    0.03       0  4998.5    0.05       0
Bank Sta=4994.3,4998.5
Exp/Cntr=0.3,0.1

Type RM Length L Ch R = 1,3083,197,197,197
BEGIN DESCRIPTION:
Mapping XS 1632476a
END DESCRIPTION:
XS GIS Cut Line= 3
      1589064.02      6923978.57      1589389.51      6923869.21
      1589623.09      6923682.35
#Sta/Elev= 30
  4552.9 1684.58  4575.4 1684.59  4601.6 1682.99  4664.6 1683.31  4712.2 1682.48
  4759.2 1683.68  4785.5 1685.14  4817.0 1685.36  4853.8 1684.99  4859.9 1683.53
  4870.4 1683.31  4880.0 1683.27  4891.3 1684.18  4901.6 1683.38  4908.0 1684.00
  4922.4 1683.99  4936.8 1683.13  4972.0 1683.77  4980.0 1683.19  4986.4 1683.92
  4998.7 1682.46  4999.0 1681.96  5002.6 1681.96  5002.9 1682.46  5007.2 1683.10
  5036.0 1682.47  5135.3 1683.47  5143.3 1682.95  5164.1 1683.58  5195.4 1683.18
#Mann=3,-1,0
  4552.9    0.05       0  4998.7    0.05       0  5002.9    0.05       0
Bank Sta=4998.7,5002.9
Exp/Cntr=0.3,0.1

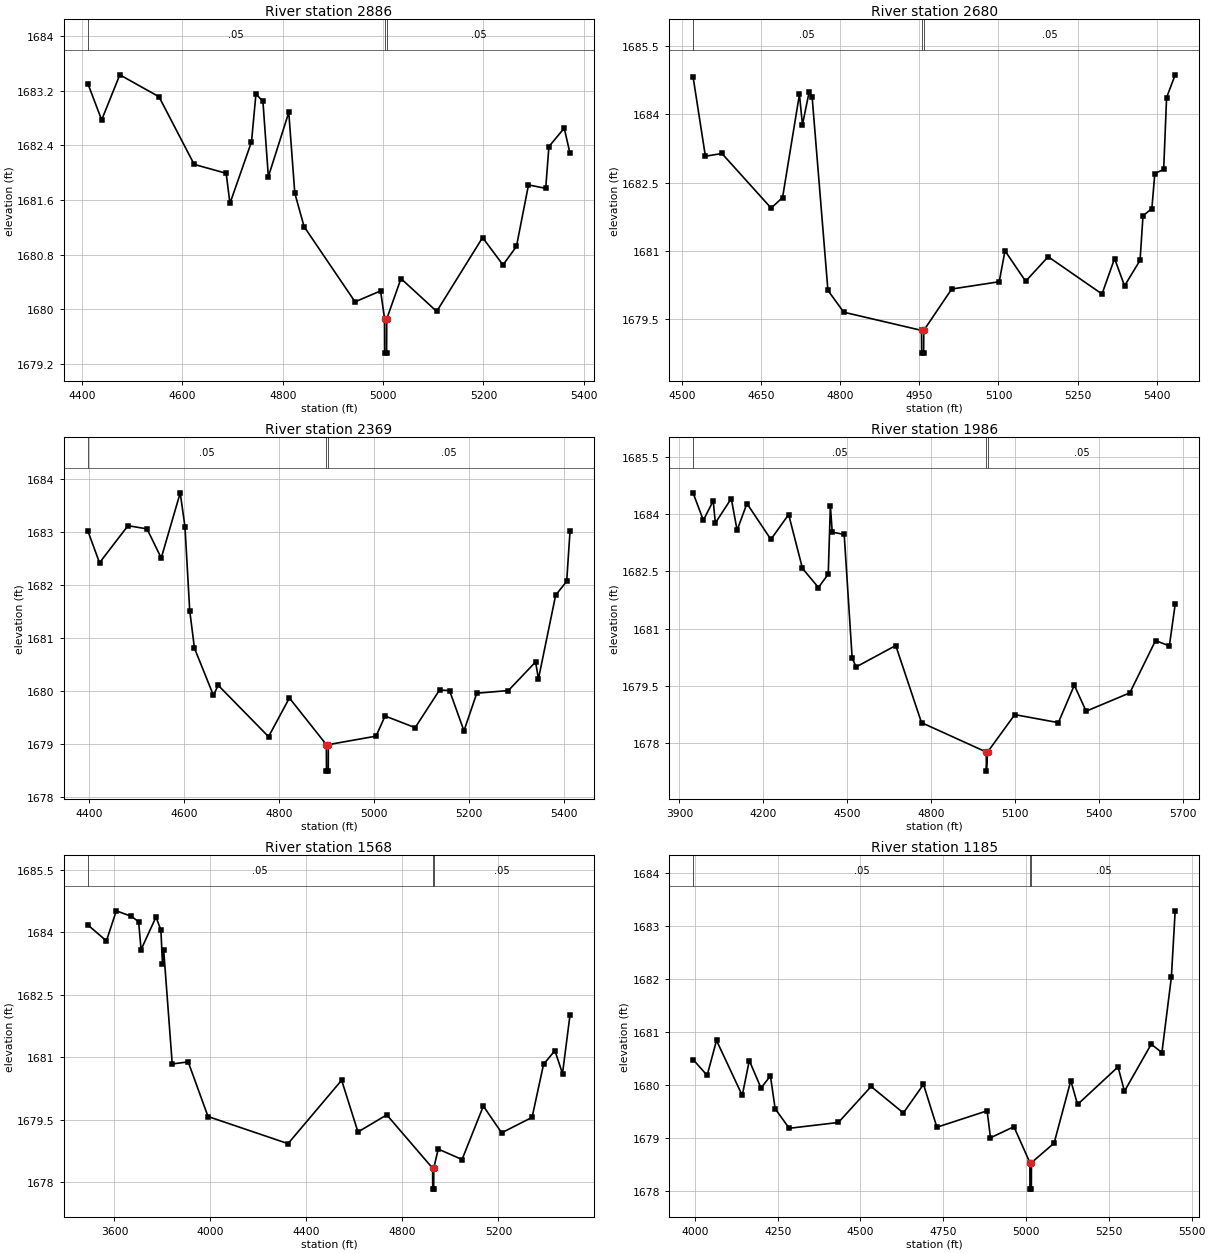
Type RM Length L Ch R = 1,2886,206,206,206
BEGIN DESCRIPTION:
Mapping XS 906472fb
END DESCRIPTION:
XS GIS Cut Line= 3
      1589006.69      6924168.70      1589261.91      6923949.94
      1589876.44      6924061.91
#Sta/Elev= 30
  4411.7 1683.30  4439.1 1682.77  4475.3 1683.43  4553.3 1683.11  4623.5 1682.12
  4687.2 1681.99  4694.8 1681.55  4737.7 1682.45  4746.6 1683.15  4760.5 1683.04
  4771.3 1681.94  4812.0 1682.88  4824.0 1681.70  4842.5 1681.21  4944.1 1680.11
  4994.9 1680.27  5003.0 1679.86  5003.3 1679.36  5007.0 1679.36  5007.2 1679.86
  5035.6 1680.45  5106.8 1679.97  5198.2 1681.05  5238.9 1680.65  5265.7 1680.92
  5289.7 1681.82  5324.0 1681.77  5330.4 1682.38  5360.9 1682.65  5372.5 1682.28
#Mann=3,-1,0
  4411.7    0.05       0  5003.0    0.03       0  5007.2    0.05       0
Bank Sta=5003,5007.2
Exp/Cntr=0.3,0.1

Type RM Length L Ch R = 1,2680,311,311,311
BEGIN DESCRIPTION:
Mapping XS e84d371c
END DESCRIPTION:
XS GIS Cut Line= 5
      1589107.16      6924233.06      1589299.49      6924125.83
      1589399.90      6924129.24      1589866.22      6924226.24
      1589970.89      6924173.90
#Sta/Elev= 30
  4521.0 1684.83  4544.4 1683.08  4575.8 1683.14  4669.0 1681.94  4690.7 1682.17
  4722.7 1684.44  4728.4 1683.77  4741.2 1684.50  4746.7 1684.39  4776.7 1680.13
  4806.7 1679.65  4954.1 1679.25  4954.4 1678.75  4958.1 1678.75  4958.4 1679.25
  5011.4 1680.16  5101.4 1680.32  5112.4 1681.00  5151.5 1680.33  5194.2 1680.87
  5296.3 1680.05  5320.1 1680.83  5339.0 1680.23  5368.4 1680.79  5374.0 1681.77
  5390.8 1681.93  5396.4 1682.70  5413.2 1682.79  5418.7 1684.37  5435.0 1684.87
#Mann=3,-1,0
  4521.0    0.05       0  4954.1    0.03       0  4958.4    0.05       0
Bank Sta=4954.1,4958.4
Exp/Cntr=0.3,0.1

Type RM Length L Ch R = 1,2369,383,383,383
BEGIN DESCRIPTION:
Mapping XS 8fd01475
END DESCRIPTION:
XS GIS Cut Line= 3
      1589030.50      6924435.48      1589637.54      6924415.64
      1589980.96      6924193.62
#Sta/Elev= 30
  4396.9 1683.01  4421.4 1682.41  4481.4 1683.11  4521.5 1683.05  4551.5 1682.50
  4591.5 1683.73  4601.5 1683.09  4611.5 1681.51  4621.5 1680.80  4661.5 1679.91
  4671.5 1680.10  4777.7 1679.13  4821.6 1679.86  4899.5 1678.98  4899.8 1678.48
  4903.5 1678.48  4903.8 1678.98  5004.3 1679.14  5023.3 1679.52  5086.7 1679.30
  5138.1 1680.01  5159.2 1680.00  5189.6 1679.24  5216.6 1679.95  5283.2 1680.00
  5340.6 1680.54  5346.6 1680.22  5382.9 1681.80  5406.1 1682.06  5413.2 1683.01
#Mann=3,-1,0
  4396.9    0.05       0  4899.5    0.03       0  4903.8    0.05       0
Bank Sta=4899.5,4903.8
Exp/Cntr=0.3,0.1

Type RM Length L Ch R = 1,1986,418,418,418
BEGIN DESCRIPTION:
Mapping XS 30871d4a
END DESCRIPTION:
XS GIS Cut Line= 4
      1588700.49      6925365.74      1589206.24      6924928.21
      1589751.36      6924456.62      1589974.48      6924208.14
#Sta/Elev= 30
  3948.8 1684.56  3985.7 1683.84  4020.9 1684.35  4028.5 1683.77  4085.5 1684.41
  4106.3 1683.58  4141.5 1684.28  4227.0 1683.34  4290.6 1683.99  4340.0 1682.58
  4397.0 1682.08  4432.1 1682.43  4439.7 1684.22  4446.4 1683.53  4489.1 1683.47
  4517.6 1680.23  4531.9 1680.00  4673.4 1680.56  4765.5 1678.54  4997.0 1677.77
  4997.4 1677.27  5001.7 1677.77  5098.9 1678.75  5254.7 1678.54  5311.7 1679.52
  5354.0 1678.84  5510.2 1679.32  5602.1 1680.69  5651.5 1680.55  5672.3 1681.64
#Mann=3,-1,0
  3948.8    0.05       0  4997.0    0.05       0  5001.7    0.05       0
Bank Sta=4997,5001.7
Exp/Cntr=0.3,0.1

Type RM Length L Ch R = 1,1568,383,383,383
BEGIN DESCRIPTION:
Mapping XS ceac62ca
END DESCRIPTION:
XS GIS Cut Line= 3
      1588740.44      6925411.07      1589726.01      6925156.40
      1590045.49      6924218.25
#Sta/Elev= 30
  3489.2 1684.17  3566.4 1683.79  3607.5 1684.51  3669.5 1684.38  3700.5 1684.25
  3710.8 1683.58  3772.8 1684.36  3793.4 1684.05  3799.9 1683.24  3805.1 1683.56
  3840.6 1680.84  3907.1 1680.89  3989.7 1679.58  4323.1 1678.93  4546.5 1680.45
  4614.5 1679.21  4734.6 1679.62  4925.7 1678.34  4926.0 1677.84  4930.1 1677.84
  4930.4 1678.34  4948.8 1678.80  5048.2 1678.55  5137.0 1679.83  5213.2 1679.19
  5340.0 1679.56  5387.8 1680.83  5435.1 1681.16  5466.8 1680.61  5498.2 1682.02
#Mann=3,-1,0
  3489.2    0.05       0  4925.7    0.03       0  4930.4    0.05       0
Bank Sta=4925.7,4930.4
Exp/Cntr=0.3,0.1

Type RM Length L Ch R = 1,1185,444,444,444
BEGIN DESCRIPTION:
Mapping XS 4118bfad
END DESCRIPTION:
XS GIS Cut Line= 3
      1589779.97      6925563.03      1590163.18      6925146.31
      1590296.48      6924266.48
#Sta/Elev= 30
  3994.3 1680.48  4036.9 1680.18  4065.2 1680.84  4142.9 1679.80  4164.2 1680.46
  4199.6 1679.94  4228.0 1680.17  4242.2 1679.55  4284.7 1679.18  4433.3 1679.29
  4532.0 1679.97  4629.5 1679.47  4690.2 1680.01  4730.7 1679.20  4882.4 1679.51
  4892.5 1679.00  4963.3 1679.21  5011.5 1678.53  5011.8 1678.03  5015.9 1678.03
  5016.3 1678.53  5084.7 1678.90  5135.1 1680.08  5155.5 1679.63  5277.7 1680.34
  5297.1 1679.88  5378.0 1680.77  5410.2 1680.61  5438.7 1682.03  5450.3 1683.29
#Mann=3,-1,0
  3994.3    0.05       0  5011.5    0.03       0  5016.3    0.05       0
Bank Sta=5011.5,5016.3
Exp/Cntr=0.3,0.1

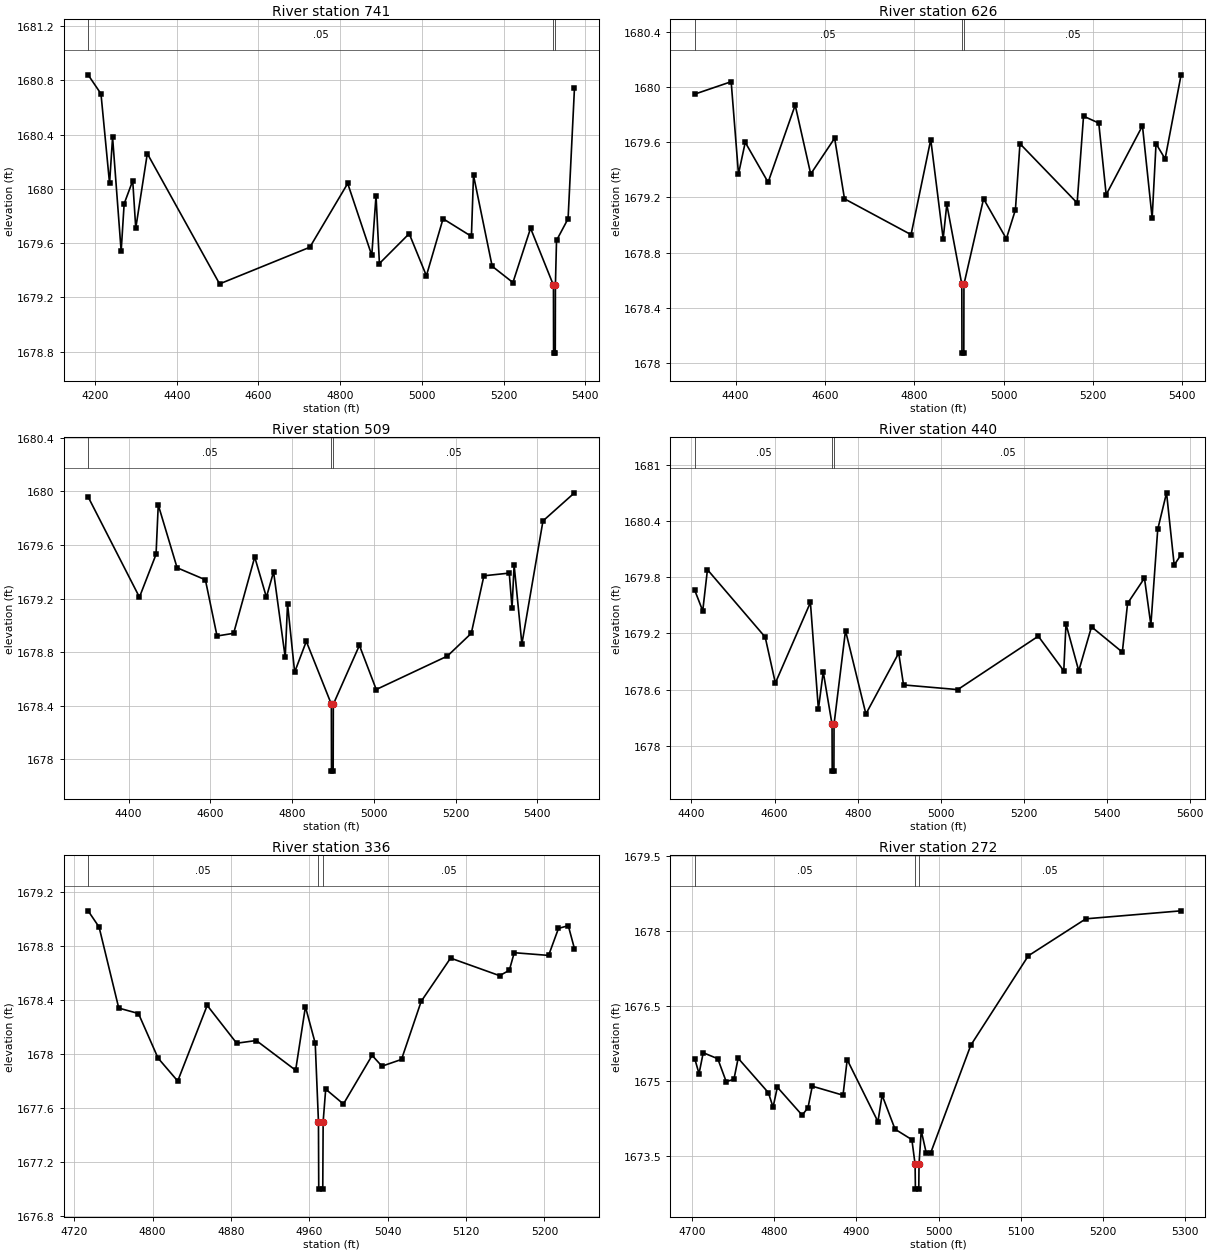
Type RM Length L Ch R = 1,741,115,115,115
BEGIN DESCRIPTION:
Mapping XS 1cfcdf76
END DESCRIPTION:
XS GIS Cut Line= 4
      1589816.85      6925554.29      1590107.65      6925241.79
      1590413.53      6925117.53      1590499.26      6924692.73
#Sta/Elev= 30
  4183.0 1680.84  4214.5 1680.70  4235.5 1680.04  4242.9 1680.38  4263.9 1679.54
  4271.2 1679.89  4292.2 1680.06  4299.6 1679.71  4327.9 1680.26  4504.8 1679.30
  4725.7 1679.57  4818.4 1680.04  4877.3 1679.51  4887.7 1679.95  4896.0 1679.45
  4968.9 1679.67  5011.0 1679.36  5051.8 1679.78  5121.2 1679.65  5126.3 1680.10
  5172.0 1679.43  5222.8 1679.31  5266.0 1679.71  5322.0 1679.29  5322.3 1678.79
  5326.4 1678.79  5326.8 1679.29  5329.5 1679.62  5357.8 1679.78  5373.4 1680.74
#Mann=3,-1,0
  4183.0    0.05       0  5322.0    0.03       0  5326.8    0.05       0
Bank Sta=5322,5326.8
Exp/Cntr=0.3,0.1

Type RM Length L Ch R = 1,626,117,117,117
BEGIN DESCRIPTION:
Mapping XS 6086a5ed
END DESCRIPTION:
XS GIS Cut Line= 5
      1589944.85      6925489.21      1590497.45      6925200.65
      1590525.24      6925059.68      1590506.09      6924948.31
      1590541.69      6924742.77
#Sta/Elev= 30
  4308.4 1679.95  4389.9 1680.04  4406.3 1679.37  4421.4 1679.60  4472.6 1679.31
  4533.2 1679.87  4568.0 1679.37  4621.5 1679.63  4643.6 1679.19  4792.6 1678.93
  4836.7 1679.62  4864.5 1678.90  4872.6 1679.15  4906.2 1678.57  4906.6 1678.07
  4910.7 1678.07  4911.0 1678.57  4954.9 1679.19  5005.9 1678.90  5026.2 1679.11
  5036.4 1679.59  5164.4 1679.16  5178.7 1679.79  5212.8 1679.74  5229.4 1679.22
  5310.6 1679.72  5332.3 1679.05  5341.0 1679.59  5361.3 1679.48  5397.1 1680.09
#Mann=3,-1,0
  4308.4    0.05       0  4906.2    0.05       0  4911.0    0.05       0
Bank Sta=4906.2,4911
Exp/Cntr=0.3,0.1

Type RM Length L Ch R = 1,509,69,69,69
BEGIN DESCRIPTION:
Mapping XS 7fa43637
END DESCRIPTION:
XS GIS Cut Line= 4
      1589991.03      6925482.92      1590612.92      6925199.51
      1590614.35      6925023.04      1590532.54      6924703.44
#Sta/Elev= 30
  4301.0 1679.96  4426.6 1679.21  4467.2 1679.53  4472.6 1679.90  4518.7 1679.43
  4587.9 1679.34  4616.4 1678.92  4657.0 1678.94  4708.6 1679.51  4737.2 1679.21
  4754.7 1679.40  4783.2 1678.76  4788.9 1679.16  4806.3 1678.65  4834.8 1678.88
  4896.1 1678.41  4896.4 1677.91  4900.5 1677.91  4900.9 1678.41  4964.7 1678.85
  5005.9 1678.52  5180.0 1678.77  5238.4 1678.94  5269.3 1679.37  5331.3 1679.39
  5338.1 1679.13  5343.2 1679.45  5362.2 1678.86  5413.8 1679.78  5490.8 1679.99
#Mann=3,-1,0
  4301.0    0.05       0  4896.1    0.05       0  4900.9    0.05       0
Bank Sta=4896.1,4900.9
Exp/Cntr=0.3,0.1

Type RM Length L Ch R = 1,440,104,104,104
BEGIN DESCRIPTION:
Mapping XS ae783118
END DESCRIPTION:
XS GIS Cut Line= 4
      1590137.09      6925432.31      1590674.80      6925223.32
      1590682.97      6925036.93      1590545.16      6924655.10
#Sta/Elev= 30
  4408.2 1679.66  4427.4 1679.44  4438.7 1679.88  4577.6 1679.16  4602.0 1678.67
  4686.3 1679.53  4705.5 1678.39  4717.1 1678.79  4738.3 1678.23  4738.7 1677.73
  4742.8 1677.73  4743.1 1678.23  4770.7 1679.23  4819.7 1678.34  4898.6 1678.99
  4910.2 1678.65  5040.5 1678.60  5234.2 1679.17  5295.5 1678.80  5300.8 1679.30
  5331.5 1678.80  5362.2 1679.27  5436.3 1679.00  5448.9 1679.52  5489.5 1679.79
  5504.9 1679.29  5521.4 1680.31  5542.6 1680.70  5561.0 1679.93  5577.6 1680.04
#Mann=3,-1,0
  4408.2    0.05       0  4738.3    0.05       0  4743.1    0.05       0
Bank Sta=4738.3,4743.1
Exp/Cntr=0.3,0.1

Type RM Length L Ch R = 1,336,64,64,64
BEGIN DESCRIPTION:
Mapping XS e25b7ebf
END DESCRIPTION:
XS GIS Cut Line= 3
      1590493.81      6925311.98      1590749.39      6925291.55
      1590736.76      6925051.68
#Sta/Elev= 30
  4734.1 1679.06  4745.3 1678.94  4765.4 1678.34  4785.5 1678.30  4805.5 1677.97
  4825.6 1677.80  4855.7 1678.36  4885.8 1678.08  4905.8 1678.10  4946.0 1677.88
  4956.0 1678.35  4966.0 1678.08  4969.3 1677.50  4969.6 1677.00  4973.7 1677.00
  4974.1 1677.50  4976.7 1677.74  4994.8 1677.63  5024.1 1677.99  5034.1 1677.91
  5054.1 1677.96  5074.2 1678.39  5104.2 1678.71  5154.3 1678.58  5164.2 1678.62
  5169.2 1678.75  5204.3 1678.73  5214.4 1678.93  5224.4 1678.95  5230.7 1678.78
#Mann=3,-1,0
  4734.1    0.05       0  4969.3    0.05       0  4974.1    0.05       0
Bank Sta=4969.3,4974.1
Exp/Cntr=0.3,0.1

Type RM Length L Ch R = 1,272,202,202,202
BEGIN DESCRIPTION:
Mapping XS 6bfa3b93
END DESCRIPTION:
XS GIS Cut Line= 3
      1590517.71      6925404.82      1590793.85      6925340.29
      1590796.84      6925032.08
#Sta/Elev= 30
  4703.4 1675.44  4708.6 1675.14  4713.7 1675.56  4731.4 1675.44  4741.7 1674.98
  4751.1 1675.03  4756.2 1675.45  4793.0 1674.76  4798.7 1674.47  4803.9 1674.87
  4834.1 1674.31  4841.2 1674.46  4846.4 1674.89  4883.8 1674.71  4888.9 1675.42
  4926.3 1674.18  4931.4 1674.71  4947.1 1674.03  4967.6 1673.82  4971.5 1673.33
  4971.9 1672.83  4976.0 1672.83  4976.3 1673.33  4979.0 1674.00  4985.0 1673.56
  4990.6 1673.56  5039.3 1675.71  5109.3 1677.50  5179.3 1678.24  5295.2 1678.40
#Mann=3,-1,0
  4703.4    0.05       0  4971.5    0.05       0  4976.3    0.05       0
Bank Sta=4971.5,4976.3
Exp/Cntr=0.3,0.1

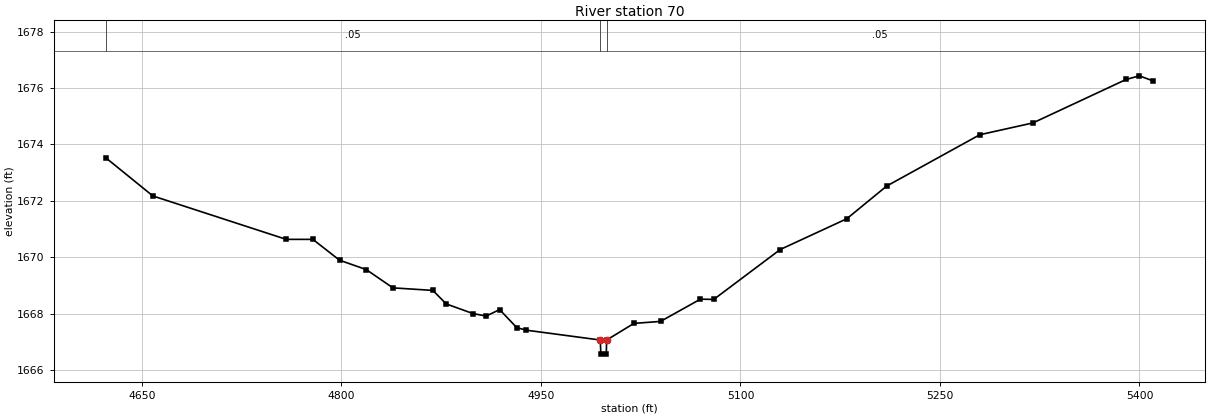
Type RM Length L Ch R = 1,70,0,0,0
BEGIN DESCRIPTION:
Deadman 10 1.0
END DESCRIPTION:
XS GIS Cut Line= 3
      1590529.74      6925461.84      1590905.94      6925487.85
      1590898.89      6925077.71
#Sta/Elev= 30
  4622.9 1673.52  4658.2 1672.17  4758.5 1670.63  4778.5 1670.63  4798.6 1669.89
  4818.6 1669.56  4838.7 1668.91  4868.7 1668.82  4878.8 1668.34  4898.8 1668.00
  4908.8 1667.91  4918.9 1668.14  4931.8 1667.50  4938.9 1667.41  4994.6 1667.06
  4995.0 1666.56  4999.1 1666.56  4999.4 1667.06  5019.9 1667.65  5039.9 1667.72
  5069.9 1668.51  5079.9 1668.50  5129.9 1670.27  5179.9 1671.36  5209.9 1672.52
  5279.9 1674.34  5319.9 1674.76  5389.9 1676.30  5399.9 1676.43  5410.2 1676.25
#Mann=3,-1,0
  4622.9    0.05       0  4994.6    0.05       0  4999.4    0.05       0
Bank Sta=4994.6,4999.4
Exp/Cntr=0.3,0.1

Chan Stop Cuts=-1