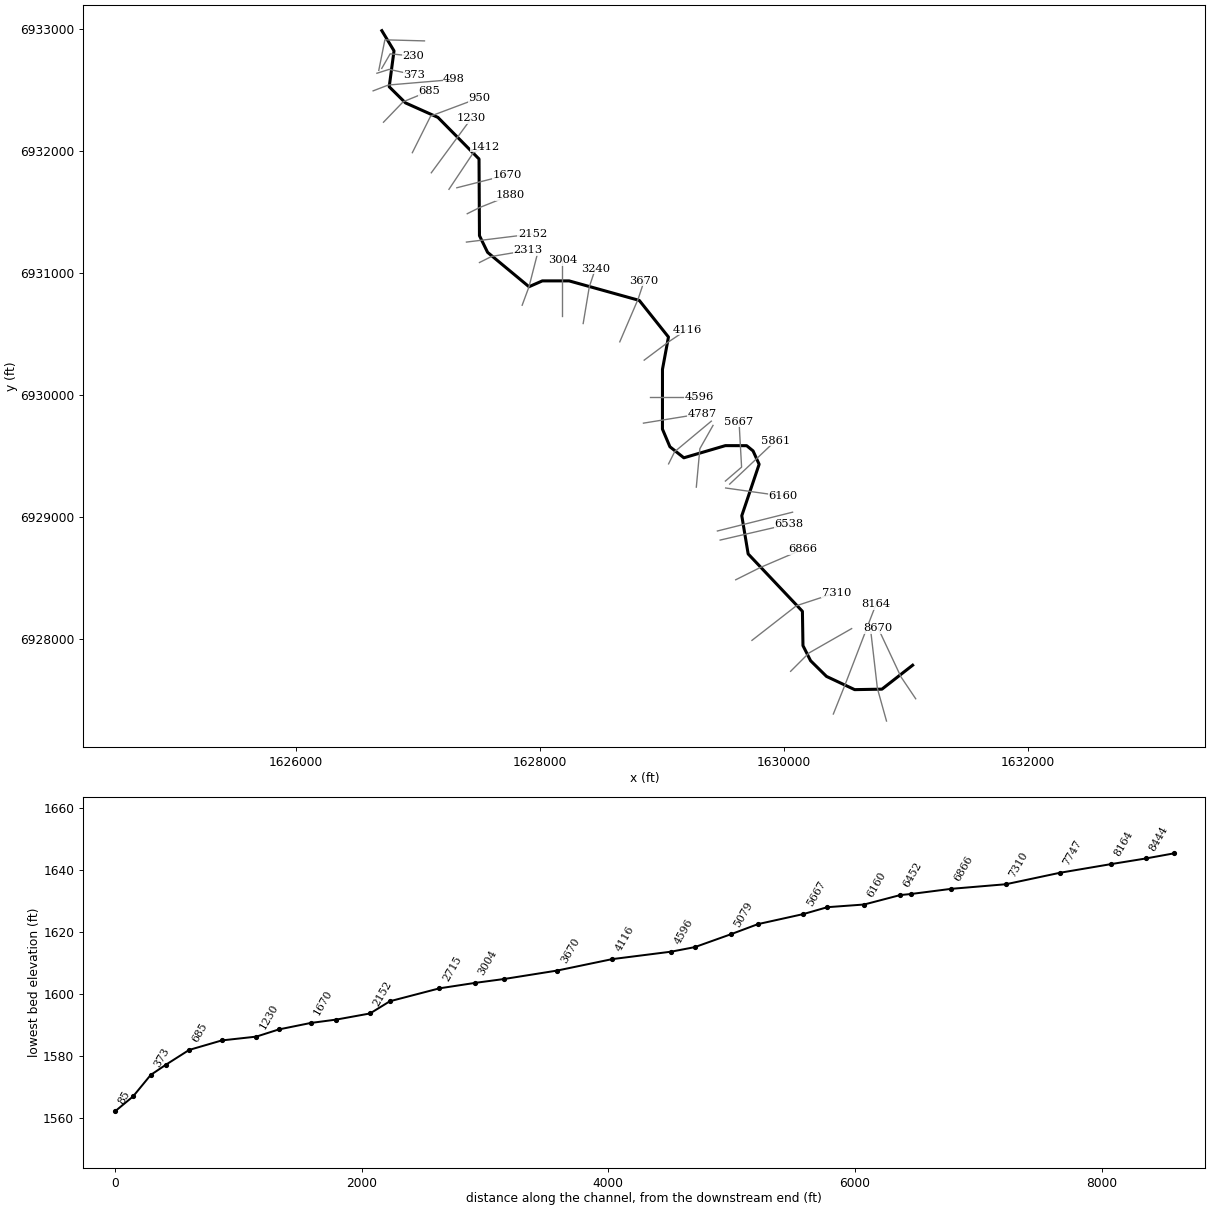
--- Deadman 11.prj (project) ---

Proj Title=Deadman 11 Base Level Engineering
Current Plan=p01
Default Exp/Contr=0.3,0.1
English Units
Geom File=g01
Flow File=f01
Plan File=p01
BEGIN DESCRIPTION:
Deadman 11
END DESCRIPTION:

--- Deadman 11.p01 (plan) ---

Plan Title=Multiple Run
Short Identifier=Multiple
Geom File=g01
Flow File=f01
Subcritical Flow
K Sum by GR= 0
Std Step Tol= 0.01
Critical Tol= 0.01
Num of Std Step Trials= 20
Max Error Tol= 0.3
Flow Tol Ratio= 0.001
Split Flow NTrial= 30
Split Flow Tol= 0.02
Split Flow Ratio= 0.02
Log Output Level= 0
Friction Slope Method= 1
Unsteady Friction Slope Method= 2
Unsteady Bridges Friction Slope Method= 1
Parabolic Critical Depth
Global Vel Dist=  1 , 1 , 1
Global Log Level= 0
CheckData=True
Encroach Param= -1, 0, 0, 0
BEGIN DESCRIPTION:
Multiple Run
END DESCRIPTION:

--- Deadman 11.f01 (steady flow) ---

Flow Title=Multiple
Number of Profiles=7
Profile Names=10-year,25-year,50-year,1pct_min,100-year,1pct_plu,500-year
River Rch & RM= Deadman 11,Reach-1,8670
     324     453     561     346     690    1376    1055
Boundary for River Rch & Prof#=Deadman 11,Reach-1,1
Up Type=0
Dn Type=3
Dn Slope=0.005
Boundary for River Rch & Prof#=Deadman 11,Reach-1,2
Up Type=0
Dn Type=3
Dn Slope=0.005
Boundary for River Rch & Prof#=Deadman 11,Reach-1,3
Up Type=0
Dn Type=3
Dn Slope=0.005
Boundary for River Rch & Prof#=Deadman 11,Reach-1,4
Up Type=0
Dn Type=3
Dn Slope=0.005
Boundary for River Rch & Prof#=Deadman 11,Reach-1,5
Up Type=0
Dn Type=3
Dn Slope=0.005
Boundary for River Rch & Prof#=Deadman 11,Reach-1,6
Up Type=0
Dn Type=3
Dn Slope=0.005
Boundary for River Rch & Prof#=Deadman 11,Reach-1,7
Up Type=0
Dn Type=3
Dn Slope=0.005

--- Deadman 11.g01 (geometry) ---

Geom Title=Existing Conditions

River Reach=Deadman 11,Reach-1
Reach XY= 30
      1631055.00      6927788.00      1630803.45      6927591.75
      1630579.91      6927587.79      1630348.94      6927696.14
      1630218.62      6927824.78      1630156.20      6927948.50
      1630151.62      6928229.62      1629706.93      6928699.95
      1629654.77      6929013.07      1629796.95      6929434.71
      1629747.02      6929544.38      1629694.72      6929587.02
      1629520.22      6929587.48      1629179.88      6929487.68
      1629065.75      6929578.29      1629004.56      6929722.82
      1629004.88      6930213.12      1629053.80      6930477.50
      1628814.79      6930777.48      1628239.78      6930937.48
      1628020.21      6930937.46      1627911.04      6930889.63
      1627571.64      6931171.32      1627505.06      6931308.03
      1627501.46      6931936.54      1627164.68      6932277.24
      1626898.94      6932396.14      1626765.47      6932528.20
      1626804.76      6932822.78      1626705.00      6932988.00

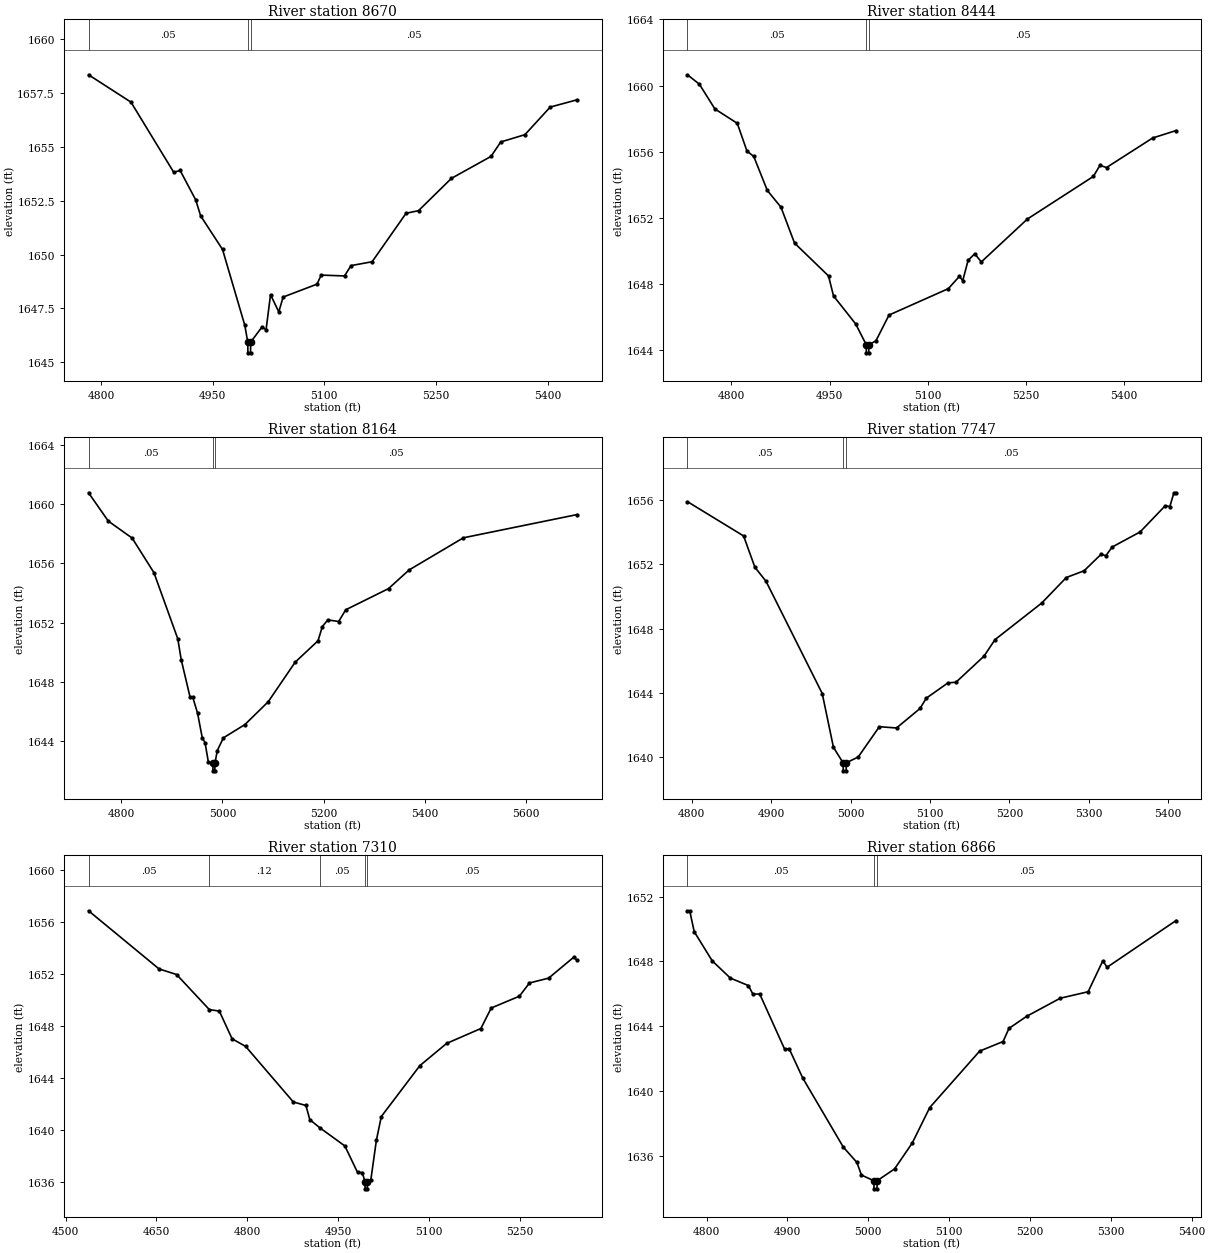
Type RM Length L Ch R = 1,8670,226,226,226
BEGIN DESCRIPTION:
Deadman 11 19.0
END DESCRIPTION:
XS GIS Cut Line= 3
      1631080.00      6927512.99      1630959.09      6927692.82
      1630772.28      6928090.98
#Sta/Elev= 30
  4783.3 1658.35  4840.3 1657.08  4897.8 1653.82  4906.3 1653.91  4927.3 1652.54
  4933.9 1651.80  4963.3 1650.24  4993.3 1646.71  4997.2 1645.94  4997.4 1645.44
  5000.9 1645.44  5001.2 1645.94  5016.3 1646.64  5021.8 1646.51  5027.8 1648.14
  5038.9 1647.34  5044.7 1648.03  5090.3 1648.63  5095.8 1649.05  5127.2 1649.01
  5135.9 1649.49  5164.3 1649.67  5209.9 1651.92  5226.6 1652.04  5270.8 1653.54
  5324.0 1654.56  5337.1 1655.23  5369.6 1655.57  5403.5 1656.85  5439.8 1657.19
#Mann=3,-1,0
  4783.3    0.05       0  4997.2    0.03       0  5001.2    0.05       0
Bank Sta=4997.2,5001.2
Exp/Cntr=0.3,0.1

Type RM Length L Ch R = 1,8444,280,280,280
BEGIN DESCRIPTION:
Mapping XS d66b1c47
END DESCRIPTION:
XS GIS Cut Line= 3
      1630840.65      6927330.47      1630766.05      6927597.80
      1630712.23      6928063.55
#Sta/Elev= 30
  4733.0 1660.65  4751.2 1660.08  4774.9 1658.58  4809.1 1657.71  4823.9 1656.03
  4834.3 1655.70  4855.0 1653.64  4875.8 1652.63  4896.6 1650.45  4948.5 1648.46
  4956.1 1647.25  4990.0 1645.55  5006.0 1644.30  5006.3 1643.80  5009.9 1643.80
  5010.1 1644.30  5020.8 1644.52  5040.9 1646.09  5131.5 1647.69  5148.5 1648.44
  5153.5 1648.17  5161.7 1649.41  5171.8 1649.80  5181.9 1649.31  5252.3 1651.91
  5353.0 1654.49  5363.1 1655.16  5373.1 1655.03  5443.6 1656.82  5479.4 1657.27
#Mann=3,-1,0
  4733.0    0.05       0  5006.0    0.03       0  5010.1    0.05       0
Bank Sta=5006,5010.1
Exp/Cntr=0.3,0.1

Type RM Length L Ch R = 1,8164,417,417,417
BEGIN DESCRIPTION:
Deadman 11 18.0
END DESCRIPTION:
XS GIS Cut Line= 3
      1630405.00      6927388.00      1630505.00      6927638.00
      1630755.01      6928288.02
#Sta/Elev= 30
  4735.3 1660.76  4774.3 1658.85  4821.5 1657.70  4864.5 1655.37  4911.7 1650.90
  4918.4 1649.50  4935.9 1646.97  4941.3 1646.95  4950.7 1645.89  4960.1 1644.21
  4965.5 1643.90  4972.2 1642.56  4981.0 1642.49  4981.2 1641.99  4984.8 1641.99
  4985.1 1642.49  4989.7 1643.36  5001.9 1644.22  5044.2 1645.11  5090.3 1646.65
  5143.8 1649.33  5188.8 1650.77  5197.4 1651.73  5208.1 1652.18  5229.6 1652.07
  5243.5 1652.86  5328.1 1654.29  5368.8 1655.55  5476.0 1657.72  5701.0 1659.29
#Mann=3,-1,0
  4735.3    0.05       0  4981.0    0.05       0  4985.1    0.05       0
Bank Sta=4981,4985.1
Exp/Cntr=0.3,0.1

Type RM Length L Ch R = 1,7747,437,437,437
BEGIN DESCRIPTION:
Deadman 11 17.0
END DESCRIPTION:
XS GIS Cut Line= 3
      1630055.00      6927738.00      1630205.00      6927888.00
      1630554.96      6928087.98
#Sta/Elev= 30
  4794.7 1655.88  4865.4 1653.75  4879.6 1651.81  4893.7 1650.93  4964.4 1643.97
  4978.5 1640.63  4990.6 1639.67  4990.9 1639.17  4994.5 1639.17  4994.7 1639.67
  5009.7 1640.03  5036.3 1641.91  5057.9 1641.83  5087.5 1643.04  5095.4 1643.68
  5122.7 1644.63  5132.8 1644.67  5168.1 1646.29  5181.8 1647.31  5240.8 1649.59
  5271.7 1651.17  5294.1 1651.59  5315.6 1652.62  5321.4 1652.52  5329.3 1653.06
  5364.6 1654.00  5396.3 1655.63  5402.0 1655.57  5407.1 1656.43  5409.9 1656.43
#Mann=3,-1,0
  4794.7    0.05       0  4990.6    0.05       0  4994.7    0.05       0
Bank Sta=4990.6,4994.7
Exp/Cntr=0.3,0.1

Type RM Length L Ch R = 1,7310,444,444,444
BEGIN DESCRIPTION:
Deadman 11 16.0
END DESCRIPTION:
XS GIS Cut Line= 3
      1629738.13      6927991.54      1630102.54      6928275.51
      1630429.82      6928383.07
#Sta/Elev= 30
  4538.0 1656.89  4654.4 1652.41  4683.3 1651.98  4737.3 1649.28  4753.9 1649.16
  4774.9 1647.03  4797.3 1646.44  4876.0 1642.16  4896.8 1641.89  4903.2 1640.80
  4919.3 1640.19  4961.1 1638.77  4981.9 1636.74  4990.0 1636.72  4994.3 1635.97
  4994.5 1635.47  4998.1 1635.47  4998.4 1635.97  5003.9 1636.16  5013.1 1639.22
  5021.2 1641.04  5084.8 1644.96  5128.9 1646.67  5185.5 1647.82  5202.6 1649.40
  5249.1 1650.31  5265.7 1651.33  5297.3 1651.70  5339.2 1653.33  5344.5 1653.06
#Mann=5,-1,0
  4538.0    0.05       0  4737.3    0.12       0  4919.3    0.05       0
  4994.3    0.05       0  4998.4    0.05       0
Bank Sta=4994.3,4998.4
Exp/Cntr=0.3,0.1

Type RM Length L Ch R = 1,6866,328,328,328
BEGIN DESCRIPTION:
Deadman 11 15.0
END DESCRIPTION:
XS GIS Cut Line= 3
      1629605.03      6928488.01      1629805.00      6928588.00
      1630155.03      6928738.01
#Sta/Elev= 30
  4776.3 1651.12  4779.1 1651.12  4784.7 1649.83  4807.0 1648.03  4829.4 1646.97
  4851.7 1646.51  4857.3 1645.98  4865.7 1645.99  4896.5 1642.59  4902.1 1642.62
  4918.8 1640.82  4969.1 1636.55  4985.9 1635.61  4991.5 1634.83  5006.8 1634.48
  5007.1 1633.98  5010.7 1633.98  5011.0 1634.48  5032.5 1635.21  5054.3 1636.80
  5076.0 1638.99  5137.7 1642.47  5166.7 1643.06  5174.0 1643.87  5195.7 1644.61
  5237.4 1645.73  5271.9 1646.13  5290.0 1648.03  5295.4 1647.64  5380.7 1650.52
#Mann=3,-1,0
  4776.3    0.05       0  5006.8    0.05       0  5011.0    0.05       0
Bank Sta=5006.8,5011
Exp/Cntr=0.3,0.1

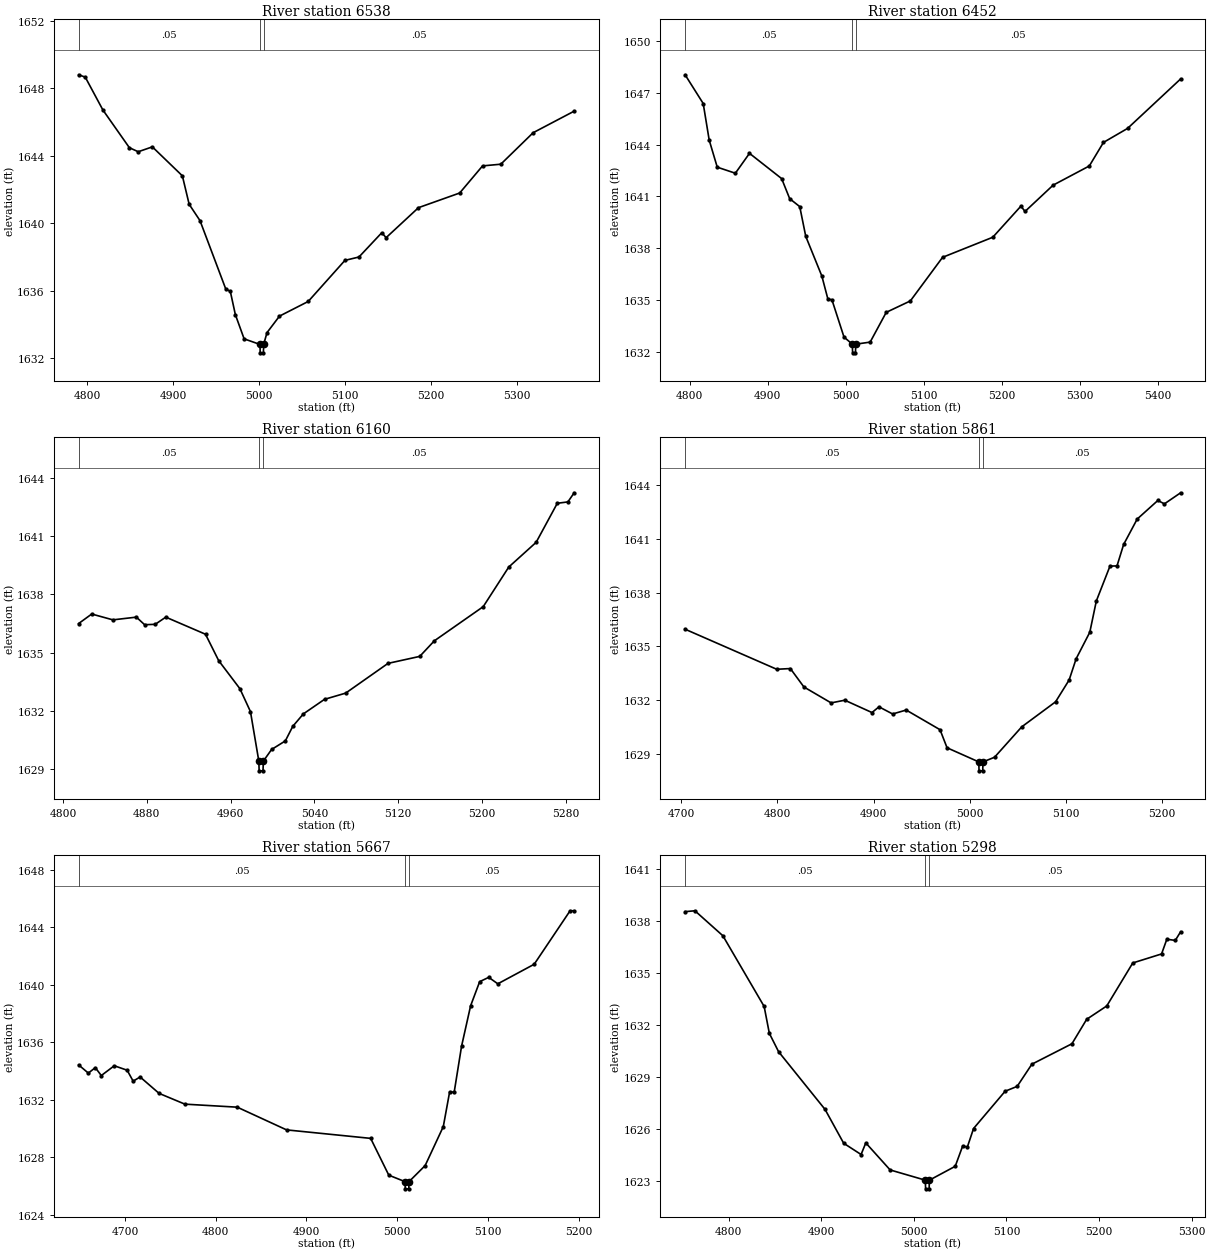
Type RM Length L Ch R = 1,6538,86,86,86
BEGIN DESCRIPTION:
Mapping XS 4f475480
END DESCRIPTION:
XS GIS Cut Line= 2
      1629477.51      6928813.46      1630038.81      6928943.19
#Sta/Elev= 30
  4790.3 1648.81  4798.0 1648.67  4818.5 1646.72  4849.3 1644.48  4859.6 1644.24
  4876.0 1644.53  4910.9 1642.81  4918.8 1641.12  4931.4 1640.15  4961.5 1636.07
  4966.6 1635.96  4972.5 1634.57  4982.7 1633.13  5001.1 1632.80  5001.4 1632.30
  5005.1 1632.30  5005.4 1632.80  5009.3 1633.50  5023.8 1634.48  5057.2 1635.35
  5099.9 1637.79  5116.2 1637.99  5142.7 1639.43  5147.8 1639.14  5185.4 1640.92
  5233.3 1641.79  5259.9 1643.40  5281.1 1643.50  5318.7 1645.37  5366.4 1646.65
#Mann=3,-1,0
  4790.3    0.05       0  5001.1    0.03       0  5005.4    0.05       0
Bank Sta=5001.1,5005.4
Exp/Cntr=0.3,0.1

Type RM Length L Ch R = 1,6452,292,292,292
BEGIN DESCRIPTION:
Deadman 11 14.0
END DESCRIPTION:
XS GIS Cut Line= 3
      1629454.99      6928888.00      1629655.00      6928938.00
      1630070.92      6929042.03
#Sta/Elev= 30
  4794.2 1648.03  4817.4 1646.37  4825.1 1644.25  4835.4 1642.69  4858.6 1642.34
  4876.7 1643.49  4917.9 1642.03  4928.2 1640.87  4941.1 1640.41  4948.8 1638.69
  4969.4 1636.40  4977.2 1635.06  4982.3 1635.03  4997.8 1632.87  5008.5 1632.46
  5008.8 1631.96  5012.5 1631.96  5012.8 1632.46  5031.3 1632.58  5051.9 1634.30
  5082.8 1634.96  5124.1 1637.48  5188.4 1638.64  5224.5 1640.44  5229.7 1640.13
  5265.7 1641.65  5312.1 1642.76  5330.2 1644.12  5361.1 1644.93  5429.1 1647.79
#Mann=3,-1,0
  4794.2    0.05       0  5008.5    0.03       0  5012.8    0.05       0
Bank Sta=5008.5,5012.8
Exp/Cntr=0.3,0.1

Type RM Length L Ch R = 1,6160,299,299,299
BEGIN DESCRIPTION:
Mapping XS 049b66ac
END DESCRIPTION:
XS GIS Cut Line= 2
      1629522.61      6929240.30      1629990.96      6929174.15
#Sta/Elev= 30
  4814.9 1636.49  4827.4 1636.98  4847.6 1636.68  4870.0 1636.82  4877.9 1636.43
  4888.0 1636.45  4898.1 1636.82  4936.0 1635.94  4948.6 1634.58  4968.8 1633.14
  4978.9 1631.96  4986.9 1629.41  4987.2 1628.91  4990.9 1628.91  4991.2 1629.41
  4999.1 1630.01  5012.2 1630.45  5019.3 1631.20  5029.4 1631.84  5049.6 1632.59
  5069.8 1632.91  5110.2 1634.44  5140.5 1634.80  5154.4 1635.60  5201.1 1637.36
  5225.5 1639.40  5251.6 1640.67  5271.8 1642.68  5281.9 1642.75  5287.9 1643.22
#Mann=3,-1,0
  4814.9    0.05       0  4986.9    0.03       0  4991.2    0.05       0
Bank Sta=4986.9,4991.2
Exp/Cntr=0.3,0.1

Type RM Length L Ch R = 1,5861,194,194,194
BEGIN DESCRIPTION:
Mapping XS 6c368501
END DESCRIPTION:
XS GIS Cut Line= 2
      1629555.74      6929272.25      1629930.46      6929626.27
#Sta/Elev= 30
  4703.9 1635.96  4799.2 1633.72  4813.4 1633.76  4827.5 1632.73  4855.8 1631.84
  4870.0 1631.99  4898.3 1631.30  4905.6 1631.62  4919.8 1631.22  4933.9 1631.44
  4969.1 1630.34  4976.4 1629.33  5009.4 1628.54  5009.7 1628.04  5013.5 1628.04
  5013.8 1628.54  5025.8 1628.80  5054.1 1630.50  5089.3 1631.90  5103.4 1633.12
  5110.7 1634.31  5124.9 1635.79  5131.7 1637.54  5145.9 1639.49  5153.2 1639.50
  5160.1 1640.70  5174.2 1642.12  5195.7 1643.16  5202.5 1642.97  5219.4 1643.59
#Mann=3,-1,0
  4703.9    0.05       0  5009.4    0.03       0  5013.8    0.05       0
Bank Sta=5009.4,5013.8
Exp/Cntr=0.3,0.1

Type RM Length L Ch R = 1,5667,369,369,369
BEGIN DESCRIPTION:
Mapping XS e6e1d7f7
END DESCRIPTION:
XS GIS Cut Line= 3
      1629520.52      6929297.13      1629653.18      6929411.13
      1629632.45      6929782.05
#Sta/Elev= 30
  4648.8 1634.44  4659.5 1633.87  4667.2 1634.25  4673.8 1633.70  4688.1 1634.38
  4702.3 1634.07  4708.9 1633.31  4716.6 1633.60  4737.5 1632.46  4766.0 1631.71
  4823.7 1631.50  4878.1 1629.92  4970.8 1629.33  4990.8 1626.77  5008.7 1626.32
  5009.0 1625.82  5012.8 1625.82  5013.1 1626.32  5030.9 1627.44  5050.9 1630.15
  5057.9 1632.57  5062.9 1632.54  5071.0 1635.73  5081.0 1638.55  5091.0 1640.23
  5101.0 1640.53  5111.0 1640.08  5151.1 1641.44  5190.7 1645.16  5195.2 1645.16
#Mann=3,-1,0
  4648.8    0.05       0  5008.7    0.05       0  5013.1    0.05       0
Bank Sta=5008.7,5013.1
Exp/Cntr=0.3,0.1

Type RM Length L Ch R = 1,5298,219,219,219
BEGIN DESCRIPTION:
Mapping XS 47468307
END DESCRIPTION:
XS GIS Cut Line= 3
      1629282.22      6929247.40      1629311.23      6929562.42
      1629418.97      6929753.03
#Sta/Elev= 30
  4752.9 1638.55  4763.5 1638.60  4793.7 1637.16  4838.3 1633.08  4843.9 1631.53
  4853.9 1630.47  4904.1 1627.14  4924.2 1625.19  4943.0 1624.54  4948.1 1625.21
  4974.4 1623.65  5012.4 1623.06  5012.7 1622.56  5016.5 1622.56  5016.8 1623.06
  5044.7 1623.86  5052.8 1625.04  5057.8 1624.97  5064.5 1626.04  5098.6 1628.19
  5111.6 1628.47  5127.5 1629.75  5170.8 1630.93  5186.7 1632.34  5208.4 1633.11
  5236.5 1635.59  5267.6 1636.11  5273.3 1636.96  5282.4 1636.89  5288.2 1637.39
#Mann=3,-1,0
  4752.9    0.05       0  5012.4    0.03       0  5016.8    0.05       0
Bank Sta=5012.4,5016.8
Exp/Cntr=0.3,0.1

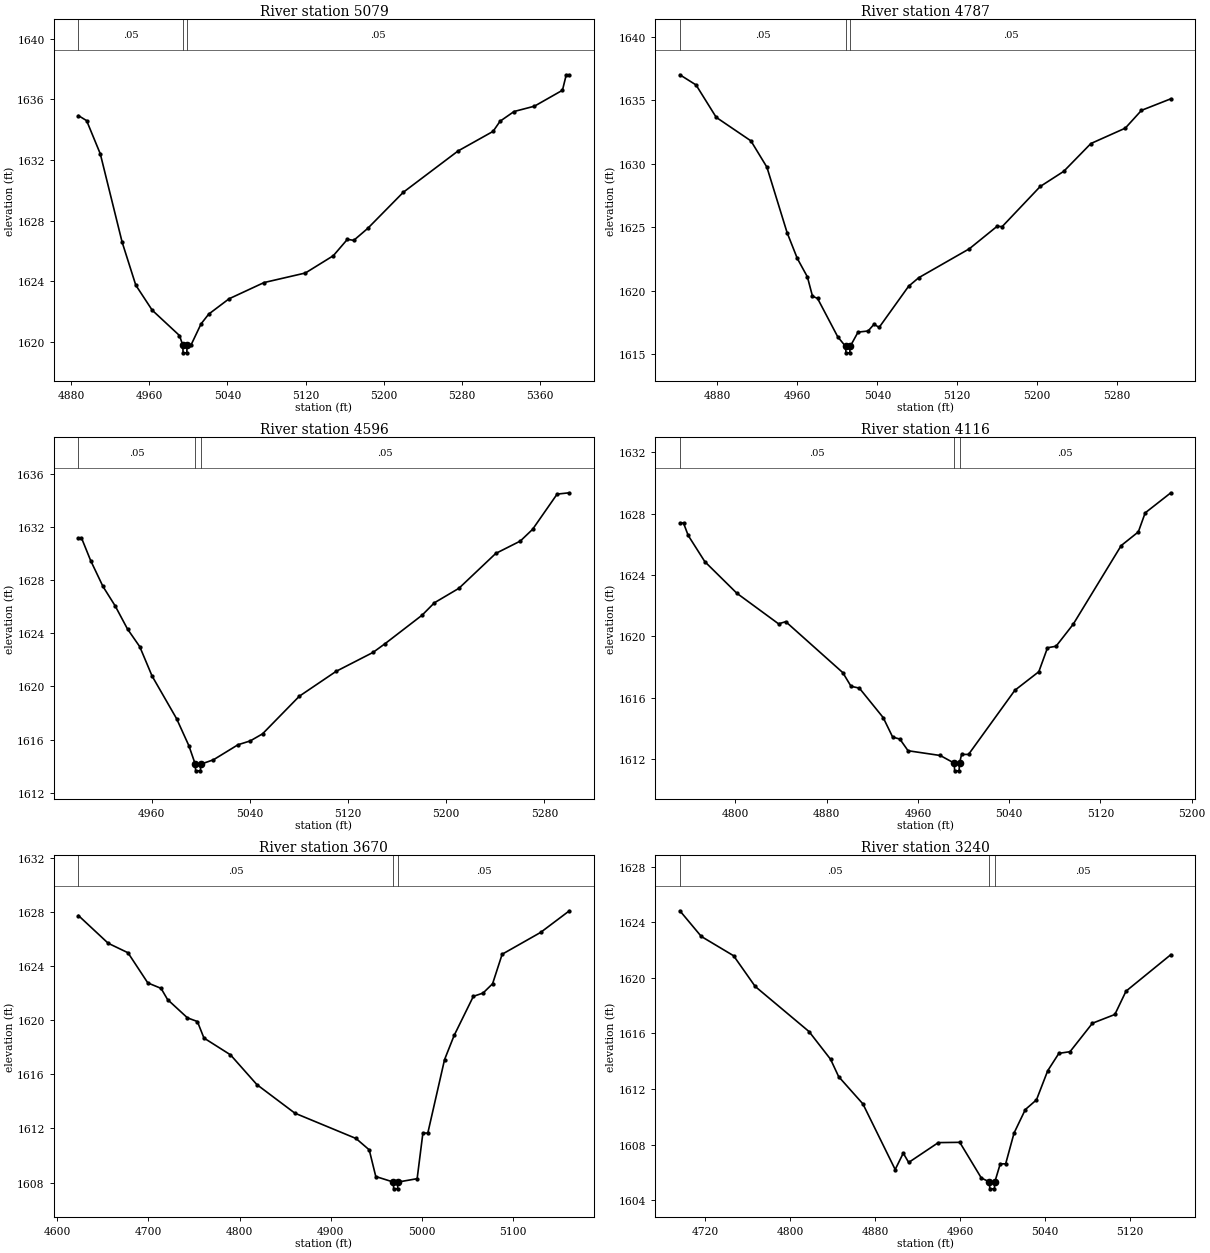
Type RM Length L Ch R = 1,5079,292,292,292
BEGIN DESCRIPTION:
Deadman 11 11.0
END DESCRIPTION:
XS GIS Cut Line= 3
      1629055.00      6929438.00      1629105.00      6929538.00
      1629404.99      6929787.99
#Sta/Elev= 30
  4887.6 1634.92  4896.0 1634.59  4910.0 1632.40  4932.3 1626.59  4946.3 1623.75
  4963.1 1622.10  4991.0 1620.43  4994.4 1619.79  4994.7 1619.29  4998.5 1619.29
  4998.8 1619.79  5002.7 1619.79  5013.1 1621.20  5020.9 1621.84  5041.7 1622.85
  5077.5 1623.92  5119.8 1624.55  5148.4 1625.69  5162.8 1626.77  5169.3 1626.70
  5183.6 1627.49  5220.0 1629.87  5276.0 1632.59  5311.8 1633.88  5319.0 1634.55
  5333.3 1635.19  5354.1 1635.54  5382.8 1636.59  5386.7 1637.61  5389.9 1637.61
#Mann=3,-1,0
  4887.6    0.05       0  4994.4    0.03       0  4998.8    0.05       0
Bank Sta=4994.4,4998.8
Exp/Cntr=0.3,0.1

Type RM Length L Ch R = 1,4787,191,191,191
BEGIN DESCRIPTION:
Mapping XS e71325e2
END DESCRIPTION:
XS GIS Cut Line= 2
      1628849.05      6929771.72      1629334.00      6929850.47
#Sta/Elev= 30
  4842.4 1637.01  4858.6 1636.21  4878.8 1633.66  4913.5 1631.81  4929.5 1629.74
  4949.7 1624.59  4959.9 1622.56  4970.0 1621.11  4975.1 1619.59  4980.2 1619.41
  5000.4 1616.39  5008.3 1615.63  5008.6 1615.13  5012.4 1615.13  5012.8 1615.63
  5020.7 1616.76  5030.8 1616.85  5036.7 1617.38  5041.8 1617.13  5071.3 1620.37
  5081.4 1621.04  5132.1 1623.32  5159.9 1625.09  5164.9 1625.06  5203.0 1628.22
  5226.5 1629.41  5253.7 1631.60  5288.1 1632.81  5304.3 1634.21  5333.7 1635.12
#Mann=3,-1,0
  4842.4    0.05       0  5008.3    0.03       0  5012.8    0.05       0
Bank Sta=5008.3,5012.8
Exp/Cntr=0.3,0.1

Type RM Length L Ch R = 1,4596,480,480,480
BEGIN DESCRIPTION:
Deadman 11 10.0
END DESCRIPTION:
XS GIS Cut Line= 3
      1628905.04      6929988.00      1629005.00      6929988.00
      1629305.04      6929988.00
#Sta/Elev= 30
  4900.3 1631.17  4902.8 1631.17  4910.3 1629.46  4920.3 1627.52  4930.3 1626.05
  4940.3 1624.32  4950.3 1622.99  4960.3 1620.79  4980.3 1617.58  4990.3 1615.55
  4995.5 1614.16  4995.8 1613.66  4999.7 1613.66  5000.0 1614.16  5010.3 1614.49
  5030.3 1615.62  5040.3 1615.91  5050.3 1616.44  5080.3 1619.27  5110.3 1621.14
  5140.3 1622.56  5150.3 1623.23  5180.3 1625.36  5190.3 1626.29  5210.3 1627.38
  5240.3 1630.00  5260.3 1630.93  5270.3 1631.81  5290.3 1634.46  5300.3 1634.56
#Mann=3,-1,0
  4900.3    0.05       0  4995.5    0.03       0  5000.0    0.05       0
Bank Sta=4995.5,5000
Exp/Cntr=0.3,0.1

Type RM Length L Ch R = 1,4116,446,446,446
BEGIN DESCRIPTION:
Deadman 11 9.0
END DESCRIPTION:
XS GIS Cut Line= 3
      1628854.96      6930287.97      1629055.00      6930438.00
      1629204.98      6930537.99
#Sta/Elev= 30
  4751.4 1627.39  4754.6 1627.39  4758.7 1626.58  4773.3 1624.87  4801.4 1622.81
  4837.9 1620.82  4844.2 1620.96  4894.2 1617.64  4901.4 1616.75  4908.7 1616.63
  4929.6 1614.71  4937.9 1613.44  4944.2 1613.31  4951.4 1612.55  4979.6 1612.24
  4991.9 1611.74  4992.2 1611.24  4996.1 1611.24  4996.5 1611.74  4998.3 1612.31
  5004.4 1612.31  5045.0 1616.49  5066.0 1617.70  5073.6 1619.26  5081.1 1619.36
  5096.1 1620.79  5138.2 1625.92  5153.2 1626.81  5159.2 1628.05  5181.7 1629.36
#Mann=3,-1,0
  4751.4    0.05       0  4991.9    0.05       0  4996.5    0.05       0
Bank Sta=4991.9,4996.5
Exp/Cntr=0.3,0.1

Type RM Length L Ch R = 1,3670,430,430,430
BEGIN DESCRIPTION:
Deadman 11 8.0
END DESCRIPTION:
XS GIS Cut Line= 3
      1628654.99      6930437.97      1628805.00      6930788.00
      1628854.99      6930937.97
#Sta/Elev= 30
  4623.1 1627.73  4655.8 1625.68  4677.5 1624.98  4699.3 1622.75  4713.8 1622.35
  4721.0 1621.52  4742.8 1620.17  4753.7 1619.90  4760.9 1618.68  4790.0 1617.44
  4819.0 1615.24  4860.7 1613.13  4927.8 1611.26  4942.3 1610.42  4949.5 1608.45
  4968.8 1608.04  4969.1 1607.54  4973.4 1607.54  4973.8 1608.04  4994.9 1608.29
  5001.2 1611.66  5006.6 1611.66  5025.0 1617.09  5035.5 1618.87  5056.6 1621.76
  5067.2 1622.00  5077.7 1622.69  5088.2 1624.87  5130.4 1626.48  5162.0 1628.08
#Mann=3,-1,0
  4623.1    0.05       0  4968.8    0.05       0  4973.8    0.05       0
Bank Sta=4968.8,4973.8
Exp/Cntr=0.3,0.1

Type RM Length L Ch R = 1,3240,236,236,236
BEGIN DESCRIPTION:
Deadman 11 7.0
END DESCRIPTION:
XS GIS Cut Line= 3
      1628355.01      6930588.04      1628405.00      6930888.00
      1628455.00      6931037.99
#Sta/Elev= 30
  4696.1 1624.84  4716.3 1622.99  4746.7 1621.60  4767.0 1619.39  4817.7 1616.14
  4838.0 1614.14  4845.6 1612.89  4868.4 1610.93  4898.8 1606.20  4906.4 1607.38
  4911.5 1606.71  4939.4 1608.14  4959.6 1608.16  4979.9 1605.59  4987.5 1605.31
  4987.9 1604.81  4992.2 1604.81  4992.6 1605.31  4997.7 1606.61  5002.8 1606.61
  5010.7 1608.83  5021.3 1610.52  5031.8 1611.22  5042.4 1613.32  5052.9 1614.57
  5063.4 1614.69  5084.5 1616.74  5105.6 1617.37  5116.1 1619.05  5158.3 1621.68
#Mann=3,-1,0
  4696.1    0.05       0  4987.5    0.05       0  4992.6    0.05       0
Bank Sta=4987.5,4992.6
Exp/Cntr=0.3,0.1

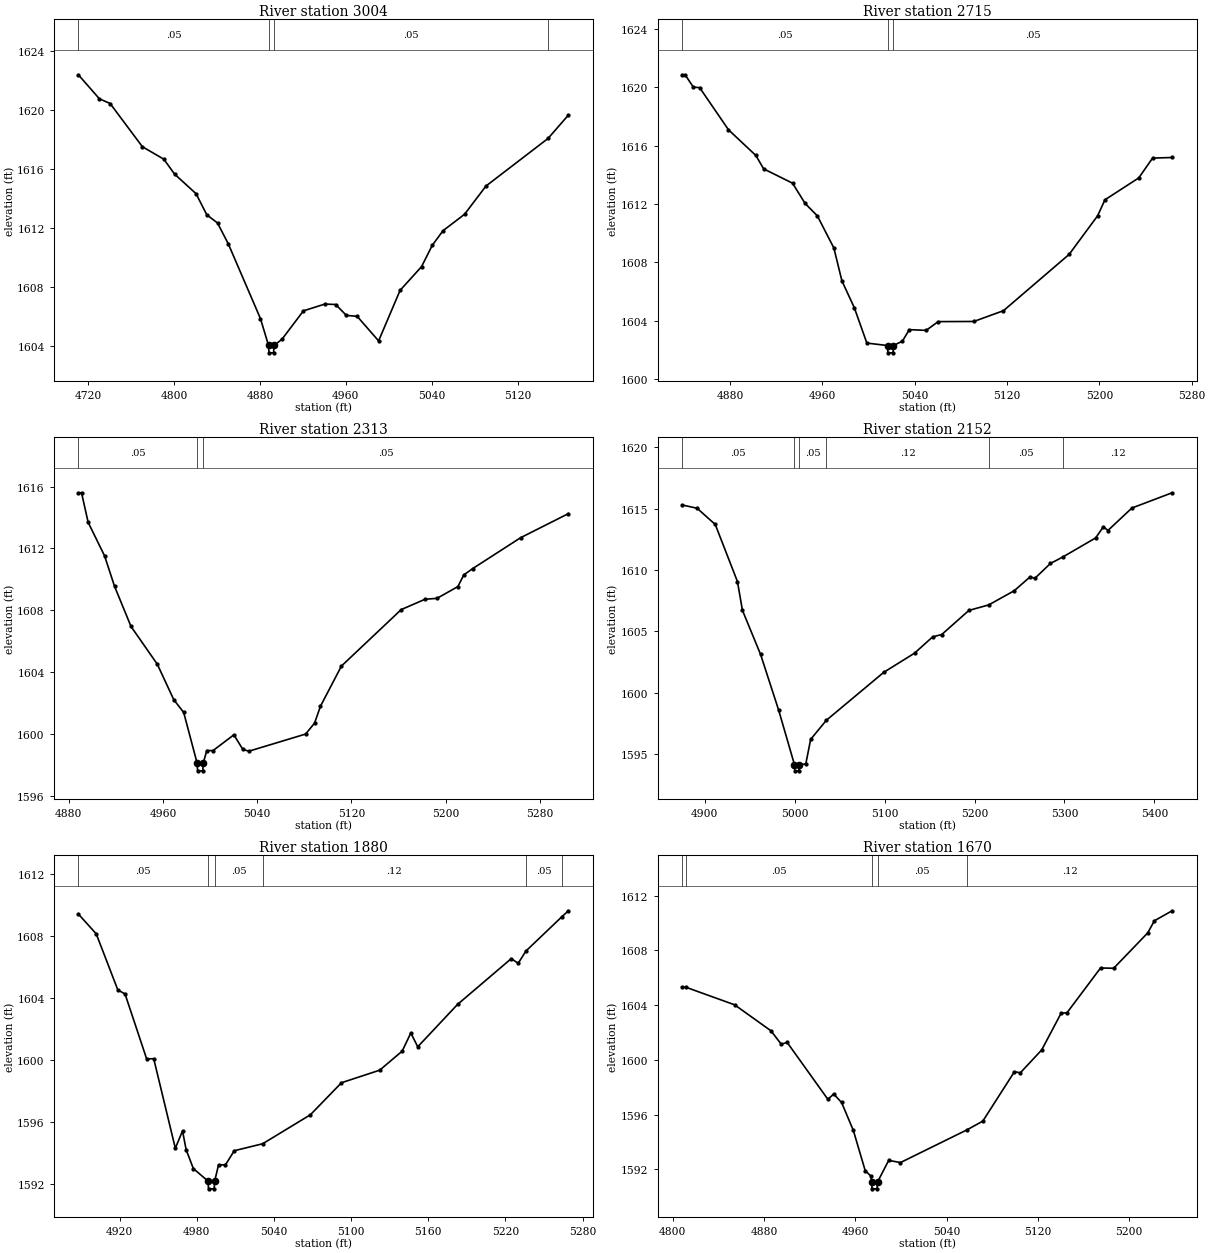
Type RM Length L Ch R = 1,3004,289,289,289
BEGIN DESCRIPTION:
Mapping XS 71c16fe3
END DESCRIPTION:
XS GIS Cut Line= 2
      1628183.85      6930648.37      1628183.85      6931104.67
#Sta/Elev= 30
  4710.9 1622.42  4730.5 1620.79  4740.5 1620.47  4770.5 1617.54  4790.5 1616.69
  4800.5 1615.68  4820.5 1614.35  4830.5 1612.92  4840.5 1612.36  4850.5 1610.95
  4880.5 1605.87  4888.0 1604.05  4888.4 1603.55  4892.7 1603.55  4893.1 1604.05
  4900.5 1604.47  4920.5 1606.40  4940.5 1606.86  4950.5 1606.83  4960.5 1606.09
  4970.5 1606.03  4990.5 1604.36  5010.5 1607.79  5030.5 1609.40  5040.5 1610.85
  5050.5 1611.84  5070.5 1612.95  5090.5 1614.87  5148.3 1618.10  5167.2 1619.68
#Mann=4,-1,0
  4710.9    0.05       0  4888.0    0.03       0  4893.1    0.05       0
  5148.3    0.12       0
Bank Sta=4888,4893.1
Exp/Cntr=0.3,0.1

Type RM Length L Ch R = 1,2715,402,402,402
BEGIN DESCRIPTION:
Deadman 11 6.0
END DESCRIPTION:
XS GIS Cut Line= 3
      1627855.02      6930738.05      1627911.04      6930889.63
      1627976.28      6931144.40
#Sta/Elev= 30
  4838.4 1620.85  4841.0 1620.85  4848.2 1620.00  4853.6 1619.97  4878.6 1617.08
  4902.3 1615.32  4909.1 1614.40  4934.1 1613.42  4945.0 1612.03  4955.6 1611.18
  4969.9 1608.98  4976.9 1606.72  4987.6 1604.89  4998.5 1602.46  5016.4 1602.29
  5016.8 1601.79  5021.2 1601.79  5021.5 1602.29  5029.3 1602.59  5035.3 1603.38
  5049.9 1603.33  5060.3 1603.93  5091.2 1603.94  5116.9 1604.68  5173.8 1608.54
  5198.5 1611.19  5204.8 1612.28  5234.1 1613.78  5246.1 1615.14  5263.0 1615.18
#Mann=3,-1,0
  4838.4    0.05       0  5016.4    0.05       0  5021.5    0.05       0
Bank Sta=5016.4,5021.5
Exp/Cntr=0.3,0.1

Type RM Length L Ch R = 1,2313,161,161,161
BEGIN DESCRIPTION:
Deadman 11 5.0
END DESCRIPTION:
XS GIS Cut Line= 3
      1627505.04      6931088.02      1627605.00      6931138.00
      1627905.01      6931188.00
#Sta/Elev= 30
  4888.2 1615.60  4890.9 1615.60  4896.5 1613.69  4910.5 1611.51  4918.9 1609.55
  4932.9 1606.95  4955.2 1604.51  4969.2 1602.21  4977.6 1601.39  4989.0 1598.11
  4989.4 1597.61  4993.8 1597.61  4994.2 1598.11  4997.2 1598.92  5002.5 1598.92
  5020.2 1599.94  5027.8 1599.00  5032.9 1598.88  5081.1 1599.99  5088.7 1600.70
  5093.7 1601.79  5111.5 1604.39  5162.2 1608.04  5182.4 1608.71  5192.6 1608.77
  5210.3 1609.53  5215.4 1610.29  5223.0 1610.70  5263.5 1612.69  5304.1 1614.25
#Mann=3,-1,0
  4888.2    0.05       0  4989.0    0.05       0  4994.2    0.05       0
Bank Sta=4989,4994.2
Exp/Cntr=0.3,0.1

Type RM Length L Ch R = 1,2152,272,272,272
BEGIN DESCRIPTION:
Mapping XS c3087dc3
END DESCRIPTION:
XS GIS Cut Line= 2
      1627398.39      6931255.55      1627939.34      6931321.87
#Sta/Elev= 30
  4874.7 1615.29  4891.4 1615.02  4911.6 1613.70  4936.3 1609.05  4941.8 1606.72
  4962.0 1603.13  4982.1 1598.60  4999.7 1594.16  5000.1 1593.66  5004.5 1593.66
  5004.9 1594.16  5012.3 1594.23  5017.7 1596.22  5035.1 1597.77  5099.1 1601.68
  5133.2 1603.23  5153.4 1604.56  5163.5 1604.75  5193.7 1606.71  5215.8 1607.16
  5244.1 1608.31  5261.9 1609.45  5266.9 1609.31  5284.4 1610.53  5298.5 1611.07
  5334.7 1612.61  5343.3 1613.52  5348.3 1613.21  5375.0 1615.04  5419.7 1616.28
#Mann=6,-1,0
  4874.7    0.05       0  4999.7    0.05       0  5004.9    0.05       0
  5035.1    0.12       0  5215.8    0.05       0  5298.5    0.12       0
Bank Sta=4999.7,5004.9
Exp/Cntr=0.3,0.1

Type RM Length L Ch R = 1,1880,210,210,210
BEGIN DESCRIPTION:
Deadman 11 4.0
END DESCRIPTION:
XS GIS Cut Line= 3
      1627405.04      6931488.02      1627505.00      6931538.00
      1627754.99      6931637.99
#Sta/Elev= 30
  4888.0 1609.43  4901.9 1608.15  4918.7 1604.53  4924.3 1604.27  4941.1 1600.08
  4946.6 1600.09  4963.4 1594.31  4969.0 1595.43  4971.8 1594.22  4977.4 1593.00
  4988.8 1592.19  4989.2 1591.69  4993.6 1591.69  4994.0 1592.19  4997.0 1593.24
  5002.4 1593.24  5009.2 1594.15  5031.3 1594.60  5068.4 1596.47  5092.6 1598.54
  5122.3 1599.35  5139.8 1600.58  5146.5 1601.75  5151.9 1600.86  5182.9 1603.60
  5224.6 1606.55  5230.0 1606.25  5236.0 1607.04  5263.9 1609.25  5269.0 1609.64
#Mann=6,-1,0
  4888.0    0.05       0  4988.8    0.03       0  4994.0    0.05       0
  5031.3    0.12       0  5236.0    0.05       0  5263.9    0.12       0
Bank Sta=4988.8,4994
Exp/Cntr=0.3,0.1

Type RM Length L Ch R = 1,1670,258,258,258
BEGIN DESCRIPTION:
Mapping XS 7a8dbf25
END DESCRIPTION:
XS GIS Cut Line= 2
      1627319.52      6931700.60      1627735.72      6931806.64
#Sta/Elev= 30
  4808.2 1605.34  4811.6 1605.31  4854.2 1604.03  4886.1 1602.13  4895.1 1601.15
  4900.3 1601.28  4936.0 1597.12  4941.1 1597.51  4948.0 1596.89  4958.3 1594.85
  4968.7 1591.91  4973.8 1591.50  4974.3 1591.08  4974.7 1590.58  4979.1 1590.58
  4979.5 1591.08  4989.3 1592.66  4999.6 1592.50  5057.9 1594.89  5071.8 1595.53
  5099.5 1599.14  5104.7 1599.06  5123.4 1600.73  5140.4 1603.41  5145.6 1603.45
  5175.0 1606.72  5186.5 1606.70  5216.3 1609.28  5222.2 1610.17  5237.7 1610.90
#Mann=5,-1,0
  4808.2    0.12       0  4811.6    0.05       0  4974.3    0.05       0
  4979.5    0.05       0  5057.9    0.12       0
Bank Sta=4974.3,4979.5
Exp/Cntr=0.3,0.1

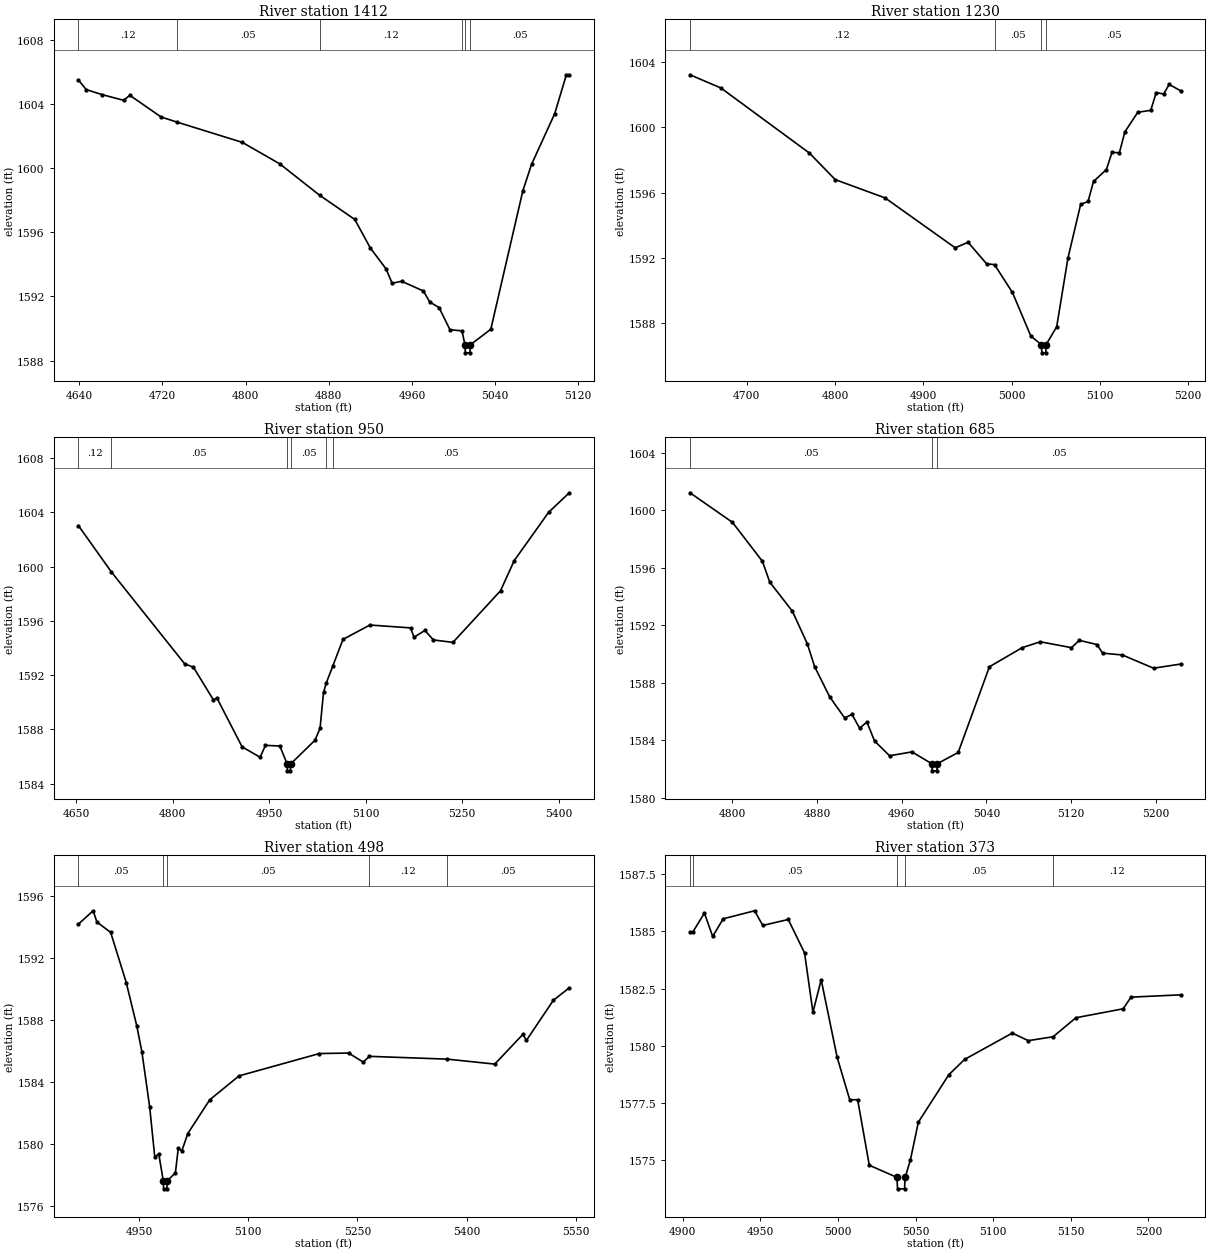
Type RM Length L Ch R = 1,1412,182,182,182
BEGIN DESCRIPTION:
Deadman 11 3.0
END DESCRIPTION:
XS GIS Cut Line= 3
      1627255.03      6931688.04      1627455.00      6931988.00
      1627554.99      6932037.99
#Sta/Elev= 30
  4639.1 1605.49  4646.6 1604.89  4661.6 1604.58  4682.6 1604.22  4688.6 1604.53
  4718.7 1603.18  4734.1 1602.86  4796.8 1601.60  4832.9 1600.26  4871.1 1598.31
  4905.0 1596.80  4920.0 1595.02  4935.0 1593.73  4941.0 1592.82  4950.0 1592.95
  4971.1 1592.34  4977.1 1591.66  4986.1 1591.31  4996.6 1589.93  5008.2 1589.86
  5011.0 1588.99  5011.4 1588.49  5015.8 1588.49  5016.2 1588.99  5035.9 1589.96
  5066.7 1598.58  5075.1 1600.23  5097.4 1603.39  5108.6 1605.81  5111.4 1605.81
#Mann=6,-1,0
  4639.1    0.12       0  4734.1    0.05       0  4871.1    0.12       0
  5008.2    0.05       0  5011.0    0.07       0  5016.2    0.05       0
Bank Sta=5011,5016.2
Exp/Cntr=0.3,0.1

Type RM Length L Ch R = 1,1230,280,280,280
BEGIN DESCRIPTION:
Mapping XS 94b574e2
END DESCRIPTION:
XS GIS Cut Line= 2
      1627110.36      6931823.39      1627439.85      6932270.99
#Sta/Elev= 30
  4635.9 1603.22  4670.9 1602.41  4771.1 1598.42  4800.4 1596.79  4856.8 1595.67
  4936.2 1592.61  4950.8 1592.95  4971.7 1591.63  4980.7 1591.58  5001.0 1589.87
  5021.8 1587.20  5033.8 1586.67  5034.3 1586.17  5038.7 1586.17  5039.1 1586.67
  5051.1 1587.77  5063.8 1591.97  5078.2 1595.27  5086.6 1595.45  5092.8 1596.68
  5107.4 1597.41  5113.7 1598.46  5122.1 1598.44  5128.3 1599.72  5142.9 1600.92
  5157.6 1601.04  5163.8 1602.13  5172.2 1602.04  5178.4 1602.63  5191.7 1602.23
#Mann=4,-1,0
  4635.9    0.12       0  4980.7    0.05       0  5033.8    0.05       0
  5039.1    0.05       0
Bank Sta=5033.8,5039.1
Exp/Cntr=0.3,0.1

Type RM Length L Ch R = 1,950,265,265,265
BEGIN DESCRIPTION:
Deadman 11 2.0
END DESCRIPTION:
XS GIS Cut Line= 3
      1626955.02      6931988.04      1627105.00      6932288.00
      1627505.04      6932438.01
#Sta/Elev= 30
  4653.8 1603.02  4704.8 1599.62  4818.7 1592.84  4832.6 1592.57  4863.4 1590.18
  4869.0 1590.31  4908.1 1586.71  4936.1 1585.94  4944.4 1586.82  4966.8 1586.77
  4978.1 1585.44  4978.5 1584.94  4983.0 1584.94  4983.4 1585.44  5021.2 1587.19
  5029.2 1588.07  5034.6 1590.72  5038.8 1591.41  5048.8 1592.64  5064.8 1594.63
  5106.6 1595.69  5169.8 1595.48  5175.2 1594.79  5192.1 1595.29  5205.4 1594.59
  5235.7 1594.41  5309.6 1598.22  5330.9 1600.44  5384.3 1604.00  5416.4 1605.44
#Mann=6,-1,0
  4653.8    0.12       0  4704.8    0.05       0  4978.1    0.05       0
  4983.4    0.05       0  5038.8    0.12       0  5048.8    0.05       0
Bank Sta=4978.1,4983.4
Exp/Cntr=0.3,0.1

Type RM Length L Ch R = 1,685,187,187,187
BEGIN DESCRIPTION:
Mapping XS dc7b12ed
END DESCRIPTION:
XS GIS Cut Line= 3
      1626718.66      6932237.84      1626880.32      6932405.73
      1627093.79      6932492.77
#Sta/Elev= 30
  4760.1 1601.23  4800.2 1599.17  4828.5 1596.46  4835.4 1595.01  4856.8 1592.98
  4870.9 1590.71  4877.8 1589.12  4892.0 1587.02  4906.1 1585.55  4913.1 1585.79
  4920.3 1584.83  4927.2 1585.26  4934.4 1583.94  4948.6 1582.91  4969.7 1583.18
  4988.4 1582.36  4988.8 1581.86  4993.3 1581.86  4993.7 1582.36  5013.4 1583.14
  5042.9 1589.11  5073.8 1590.44  5090.9 1590.85  5120.4 1590.44  5127.8 1590.95
  5144.4 1590.66  5149.8 1590.06  5168.5 1589.93  5197.9 1589.01  5223.7 1589.30
#Mann=3,-1,0
  4760.1    0.05       0  4988.4    0.05       0  4993.7    0.05       0
Bank Sta=4988.4,4993.7
Exp/Cntr=0.3,0.1

Type RM Length L Ch R = 1,498,125,125,125
BEGIN DESCRIPTION:
Mapping XS d0483eb6
END DESCRIPTION:
XS GIS Cut Line= 3
      1626633.66      6932494.82      1626758.05      6932542.51
      1627296.91      6932588.10
#Sta/Elev= 30
  4866.9 1594.16  4887.1 1595.02  4892.4 1594.29  4911.2 1593.63  4932.6 1590.40
  4947.1 1587.60  4954.0 1585.96  4964.7 1582.42  4971.8 1579.15  4977.2 1579.38
  4983.5 1577.62  4983.9 1577.12  4988.4 1577.12  4988.8 1577.62  5000.1 1578.16
  5004.0 1579.72  5009.0 1579.57  5017.1 1580.68  5047.2 1582.85  5087.4 1584.39
  5197.8 1585.83  5237.9 1585.86  5258.0 1585.28  5266.5 1585.65  5373.3 1585.47
  5438.6 1585.15  5477.1 1587.06  5482.1 1586.68  5518.9 1589.25  5540.9 1590.06
#Mann=5,-1,0
  4866.9    0.05       0  4983.5    0.05       0  4988.8    0.05       0
  5266.5    0.12       0  5373.3    0.05       0
Bank Sta=4983.5,4988.8
Exp/Cntr=0.3,0.1

Type RM Length L Ch R = 1,373,143,143,143
BEGIN DESCRIPTION:
Mapping XS e073cef0
END DESCRIPTION:
XS GIS Cut Line= 3
      1626664.61      6932639.09      1626765.39      6932670.92
      1626971.07      6932626.09
#Sta/Elev= 30
  4904.7 1584.96  4906.4 1584.96  4914.0 1585.80  4919.3 1584.78  4926.1 1585.55
  4946.3 1585.90  4951.6 1585.26  4968.0 1585.52  4978.5 1584.06  4983.9 1581.47
  4989.2 1582.89  4999.5 1579.50  5007.6 1577.65  5012.7 1577.65  5020.2 1574.79
  5038.0 1574.26  5038.4 1573.76  5042.9 1573.76  5043.3 1574.26  5046.7 1575.03
  5051.8 1576.67  5071.4 1578.74  5081.6 1579.41  5112.3 1580.56  5122.6 1580.23
  5138.6 1580.40  5153.3 1581.23  5183.7 1581.62  5188.8 1582.13  5220.9 1582.23
#Mann=5,-1,0
  4904.7    0.12       0  4906.4    0.05       0  5038.0    0.05       0
  5043.3    0.05       0  5138.6    0.12       0
Bank Sta=5038,5043.3
Exp/Cntr=0.3,0.1

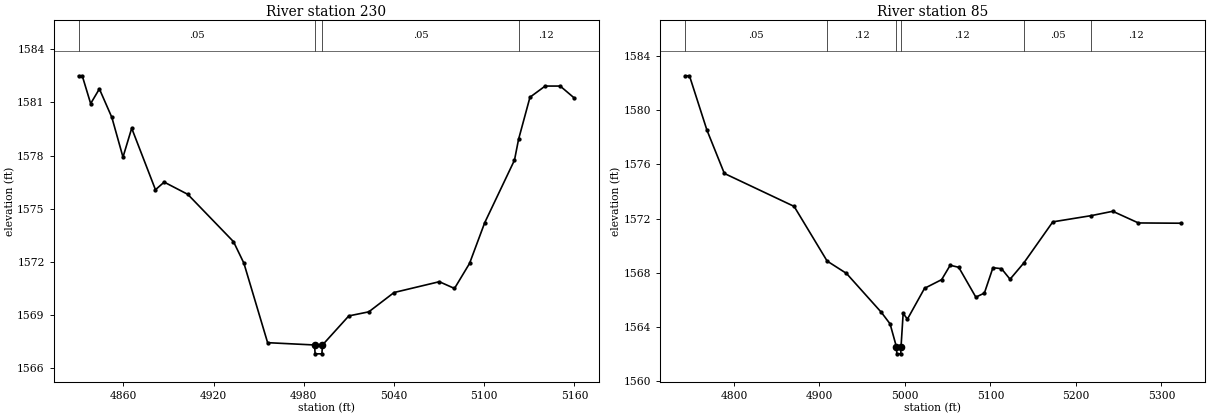
Type RM Length L Ch R = 1,230,145,145,145
BEGIN DESCRIPTION:
Mapping XS f2a08016
END DESCRIPTION:
XS GIS Cut Line= 3
      1626704.40      6932678.86      1626773.34      6932798.18
      1626964.24      6932779.62
#Sta/Elev= 30
  4830.2 1582.50  4832.6 1582.50  4838.2 1580.93  4844.0 1581.76  4852.3 1580.15
  4859.7 1577.91  4865.5 1579.54  4881.3 1576.07  4887.1 1576.50  4902.8 1575.81
  4933.2 1573.14  4940.1 1571.93  4955.9 1567.44  4987.1 1567.31  4987.5 1566.81
  4992.0 1566.81  4992.4 1567.31  5009.9 1568.95  5023.2 1569.18  5040.0 1570.27
  5070.1 1570.88  5080.2 1570.50  5090.2 1571.91  5100.3 1574.21  5120.1 1577.74
  5122.8 1578.91  5130.4 1581.29  5140.5 1581.92  5150.5 1581.92  5159.8 1581.25
#Mann=4,-1,0
  4830.2    0.05       0  4987.1    0.05       0  4992.4    0.05       0
  5122.8    0.12       0
Bank Sta=4987.1,4992.4
Exp/Cntr=0.3,0.1

Type RM Length L Ch R = 1,85,0,0,0
BEGIN DESCRIPTION:
Deadman 11 1.0
END DESCRIPTION:
XS GIS Cut Line= 3
      1626679.99      6932662.97      1626730.00      6932913.00
      1627054.40      6932904.22
#Sta/Elev= 30
  4742.9 1582.53  4748.0 1582.53  4768.4 1578.53  4788.8 1575.33  4870.4 1572.90
  4909.0 1568.87  4931.6 1567.96  4972.4 1565.09  4982.6 1564.24  4990.1 1562.53
  4990.5 1562.03  4995.0 1562.03  4995.4 1562.53  4997.9 1565.01  5002.9 1564.59
  5022.9 1566.86  5042.9 1567.50  5052.9 1568.56  5062.9 1568.41  5082.9 1566.21
  5092.9 1566.51  5102.9 1568.38  5112.9 1568.31  5122.9 1567.53  5139.0 1568.73
  5172.9 1571.76  5217.9 1572.22  5243.0 1572.54  5273.0 1571.68  5322.4 1571.66
#Mann=6,-1,0
  4742.9    0.05       0  4909.0    0.12       0  4990.1    0.07       0
  4995.4    0.12       0  5139.0    0.05       0  5217.9    0.12       0
Bank Sta=4990.1,4995.4
Exp/Cntr=0.3,0.1

Chan Stop Cuts=-1