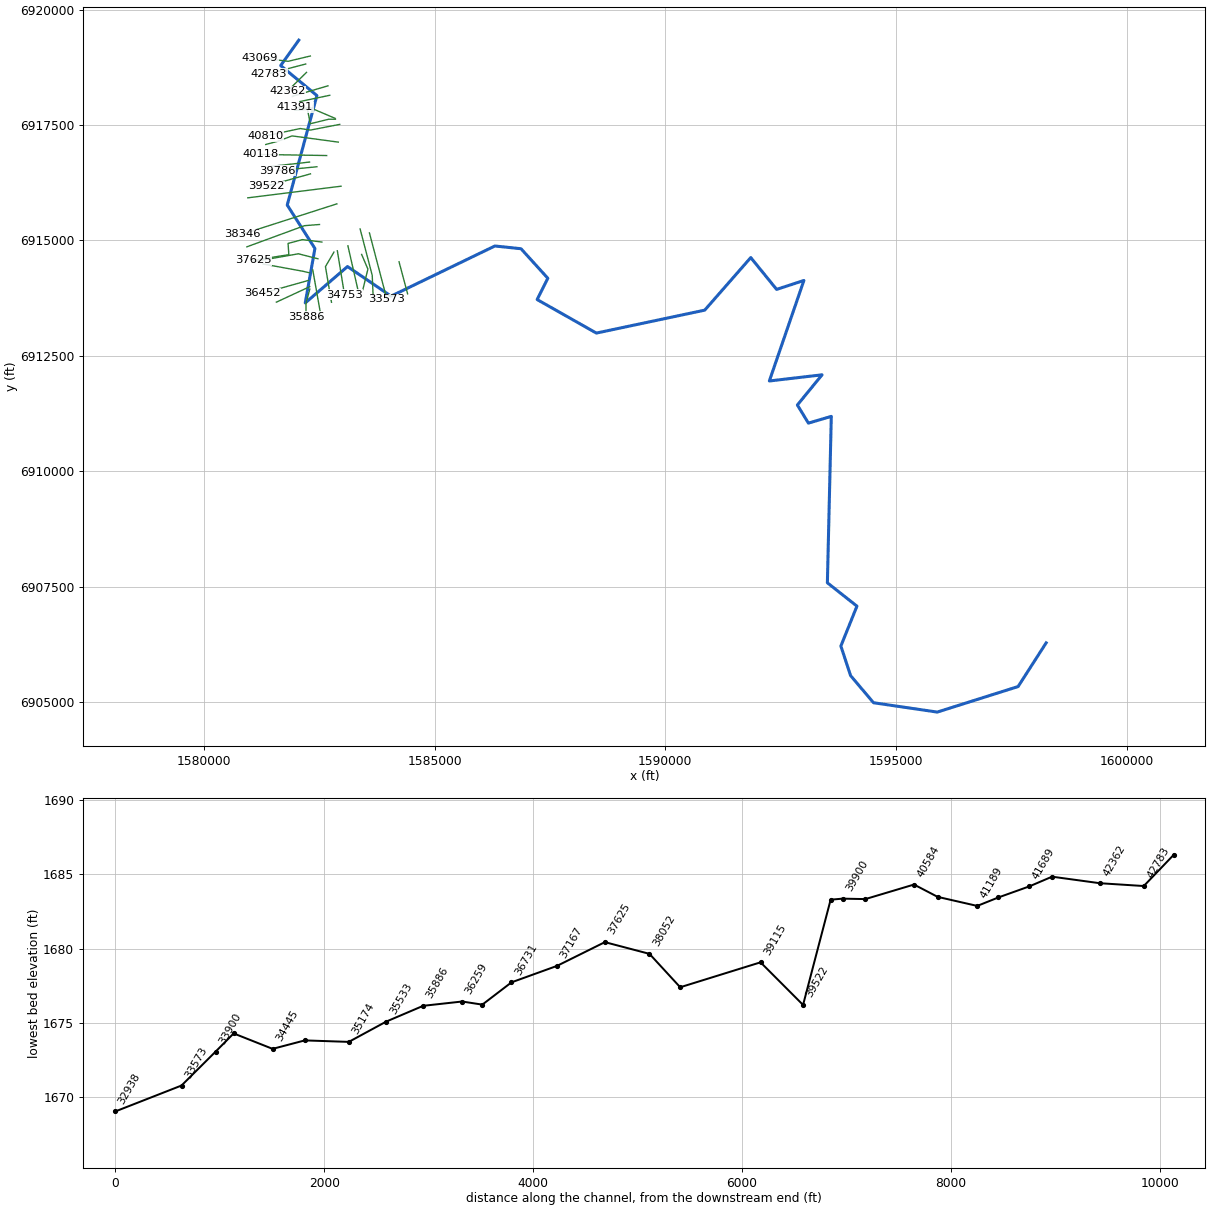
--- Deadman 12.prj (project) ---

Proj Title=Deadman 12 Base Level Engineering
Current Plan=p01
Default Exp/Contr=0.3,0.1
English Units
Geom File=g01
Flow File=f01
Plan File=p01
BEGIN DESCRIPTION:
Deadman 12
END DESCRIPTION:

--- Deadman 12.p01 (plan) ---

Plan Title=Multiple Run
Short Identifier=Multiple
Geom File=g01
Flow File=f01
Subcritical Flow
K Sum by GR= 0
Std Step Tol= 0.01
Critical Tol= 0.01
Num of Std Step Trials= 20
Max Error Tol= 0.3
Flow Tol Ratio= 0.001
Split Flow NTrial= 30
Split Flow Tol= 0.02
Split Flow Ratio= 0.02
Log Output Level= 0
Friction Slope Method= 1
Unsteady Friction Slope Method= 2
Unsteady Bridges Friction Slope Method= 1
Parabolic Critical Depth
Global Vel Dist=  1 , 1 , 1
Global Log Level= 0
CheckData=True
Encroach Param= -1, 0, 0, 0
BEGIN DESCRIPTION:
Multiple Run
END DESCRIPTION:

--- Deadman 12.f01 (steady flow) ---

Flow Title=Multiple
Number of Profiles=7
Profile Names=10-year,25-year,50-year,1pct_min,100-year,1pct_plu,500-year
River Rch & RM= Deadman 12,Reach-1,43069
      89     112     128      73     145     289     190
River Rch & RM= Deadman 12,Reach-1,40810
     109     138     159      91     181     362     240
River Rch & RM= Deadman 12,Reach-1,38346
     157     204     240     140     279     558     384
River Rch & RM= Deadman 12,Reach-1,30739
     180     237     280     164     328     655     457
River Rch & RM= Deadman 12,Reach-1,29215
     219     290     346     205     409     817     579
River Rch & RM= Deadman 12,Reach-1,24728
     282     382     461     277     552    1101     801
River Rch & RM= Deadman 12,Reach-1,21382
     303     411     498     299     597    1191     870
River Rch & RM= Deadman 12,Reach-1,19959
     330     450     547     330     658    1312     965
River Rch & RM= Deadman 12,Reach-1,15505
     354     485     591     357     712    1421    1051
River Rch & RM= Deadman 12,Reach-1,13057
     373     513     627     380     758    1511    1122
River Rch & RM= Deadman 12,Reach-1,10751
     427     593     729     444     886    1768    1329
Boundary for River Rch & Prof#=Deadman 12,Reach-1,1
Up Type=0
Dn Type=3
Dn Slope=0.005
Boundary for River Rch & Prof#=Deadman 12,Reach-1,2
Up Type=0
Dn Type=3
Dn Slope=0.005
Boundary for River Rch & Prof#=Deadman 12,Reach-1,3
Up Type=0
Dn Type=3
Dn Slope=0.005
Boundary for River Rch & Prof#=Deadman 12,Reach-1,4
Up Type=0
Dn Type=3
Dn Slope=0.005
Boundary for River Rch & Prof#=Deadman 12,Reach-1,5
Up Type=0
Dn Type=3
Dn Slope=0.005
Boundary for River Rch & Prof#=Deadman 12,Reach-1,6
Up Type=0
Dn Type=3
Dn Slope=0.005
Boundary for River Rch & Prof#=Deadman 12,Reach-1,7
Up Type=0
Dn Type=3
Dn Slope=0.005

--- Deadman 12.g01 (geometry) ---

Geom Title=Existing Conditions

River Reach=Deadman 12,Reach-1
Reach XY= 30
      1582055.00      6919338.00      1581662.18      6918788.27
      1582447.47      6918138.01      1581804.42      6915767.58
      1582404.46      6914827.31      1582194.89      6913648.04
      1583110.86      6914435.95      1584054.78      6913794.99
      1586305.22      6914881.01      1586871.70      6914821.72
      1587452.95      6914182.14      1587221.44      6913721.21
      1588504.92      6912995.30      1590853.53      6913491.55
      1591851.77      6914630.17      1592412.54      6913941.05
      1593003.54      6914134.47      1592254.88      6911958.26
      1593396.98      6912091.31      1592862.08      6911438.00
      1593101.38      6911045.47      1593597.54      6911191.61
      1593512.53      6907588.01      1594153.33      6907081.95
      1593804.89      6906217.90      1594015.97      6905577.62
      1594512.95      6904990.82      1595894.37      6904788.55
      1597646.68      6905341.15      1598255.00      6906288.00

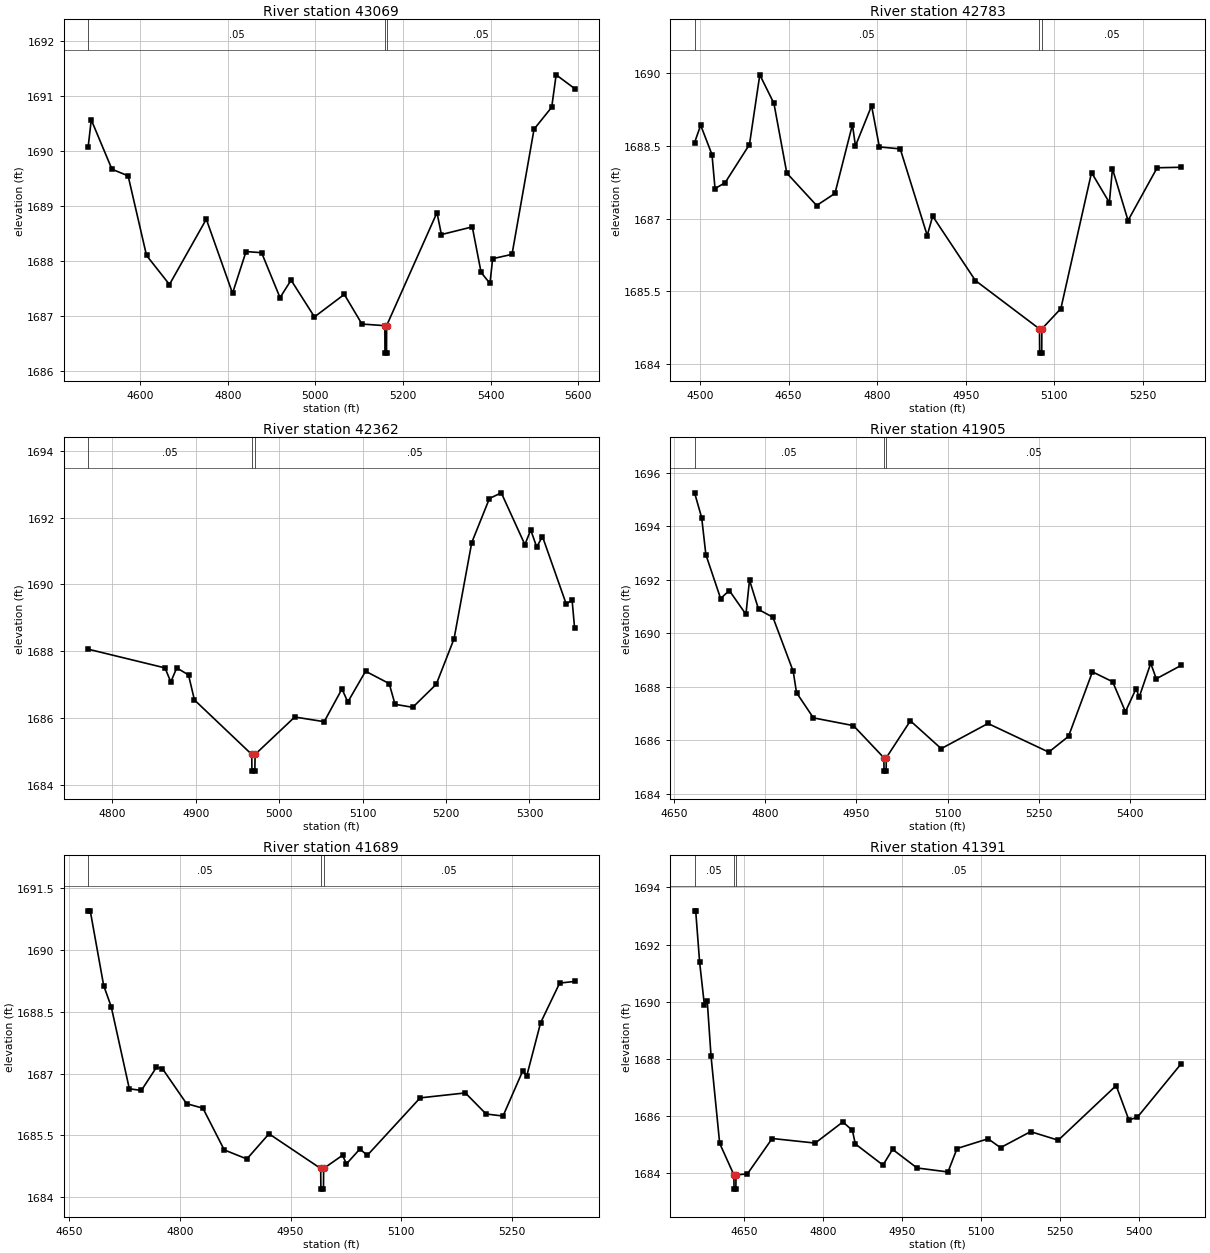
Type RM Length L Ch R = 1,43069,286,286,286
BEGIN DESCRIPTION:
Mapping XS 1027dd52
END DESCRIPTION:
XS GIS Cut Line= 3
      1582305.62      6918994.98      1581826.42      6918880.39
      1581213.13      6918955.66
#Sta/Elev= 30
  4481.2 1690.07  4488.4 1690.57  4535.6 1689.67  4572.5 1689.55  4614.5 1688.10
  4666.9 1687.57  4751.0 1688.76  4810.9 1687.41  4841.7 1688.17  4877.2 1688.15
  4919.3 1687.33  4944.5 1687.65  4997.9 1686.98  5066.0 1687.39  5106.3 1686.85
  5158.6 1686.82  5158.9 1686.32  5162.4 1686.32  5162.6 1686.82  5277.6 1688.88
  5287.7 1688.48  5358.2 1688.62  5378.3 1687.79  5398.5 1687.59  5404.7 1688.04
  5448.9 1688.12  5499.2 1690.40  5539.5 1690.80  5549.6 1691.39  5591.8 1691.14
#Mann=3,-1,0
  4481.2    0.05       0  5158.6    0.05       0  5162.6    0.05       0
Bank Sta=5158.6,5162.6
Exp/Cntr=0.3,0.1

Type RM Length L Ch R = 1,42783,421,421,421
BEGIN DESCRIPTION:
Mapping XS a2e4d895
END DESCRIPTION:
XS GIS Cut Line= 2
      1582204.93      6918821.38      1581408.10      6918613.51
#Sta/Elev= 30
  4490.9 1688.57  4501.2 1688.93  4520.4 1688.32  4525.5 1687.62  4542.5 1687.74
  4583.8 1688.53  4601.3 1689.97  4625.2 1689.38  4647.0 1687.94  4697.5 1687.27
  4728.5 1687.52  4758.1 1688.94  4763.2 1688.50  4790.5 1689.33  4803.7 1688.48
  4839.0 1688.44  4884.7 1686.65  4893.9 1687.05  4966.2 1685.72  5074.7 1684.72
  5075.0 1684.22  5078.5 1684.22  5078.7 1684.72  5110.9 1685.14  5162.8 1687.95
  5193.0 1687.33  5198.2 1688.03  5224.6 1686.96  5273.9 1688.05  5314.4 1688.06
#Mann=3,-1,0
  4490.9    0.05       0  5074.7    0.05       0  5078.7    0.05       0
Bank Sta=5074.7,5078.7
Exp/Cntr=0.3,0.1

Type RM Length L Ch R = 1,42362,457,457,457
BEGIN DESCRIPTION:
Mapping XS 6534dc12
END DESCRIPTION:
XS GIS Cut Line= 2
      1582222.29      6918640.84      1581806.60      6918232.08
#Sta/Elev= 30
  4771.1 1688.06  4863.2 1687.50  4870.2 1687.08  4877.3 1687.50  4891.4 1687.29
  4898.5 1686.54  4967.2 1684.91  4967.4 1684.41  4970.9 1684.41  4971.2 1684.91
  5018.7 1686.03  5054.0 1685.89  5075.3 1686.87  5082.3 1686.48  5103.6 1687.40
  5131.9 1687.03  5138.9 1686.41  5160.1 1686.32  5188.3 1687.01  5209.6 1688.37
  5230.8 1691.25  5252.0 1692.57  5266.2 1692.74  5294.5 1691.19  5301.5 1691.63
  5308.6 1691.12  5315.6 1691.43  5343.9 1689.42  5351.1 1689.52  5354.1 1688.68
#Mann=3,-1,0
  4771.1    0.05       0  4967.2    0.05       0  4971.2    0.05       0
Bank Sta=4967.2,4971.2
Exp/Cntr=0.3,0.1

Type RM Length L Ch R = 1,41905,216,216,216
BEGIN DESCRIPTION:
Mapping XS 1574927e
END DESCRIPTION:
XS GIS Cut Line= 2
      1582686.20      6918348.74      1581917.06      6918122.58
#Sta/Elev= 30
  4683.2 1695.25  4694.9 1694.32  4701.8 1692.94  4726.1 1691.30  4740.4 1691.60
  4767.8 1690.71  4773.7 1691.99  4788.7 1690.89  4812.3 1690.60  4845.7 1688.58
  4851.2 1687.78  4879.0 1686.84  4945.0 1686.55  4995.1 1685.35  4995.4 1684.85
  4998.9 1684.85  4999.1 1685.35  5038.8 1686.73  5089.6 1685.69  5166.7 1686.63
  5266.8 1685.56  5299.4 1686.15  5338.8 1688.56  5372.1 1688.19  5393.2 1687.07
  5410.7 1687.93  5415.9 1687.62  5434.9 1688.88  5444.0 1688.30  5484.9 1688.80
#Mann=3,-1,0
  4683.2    0.05       0  4995.1    0.05       0  4999.1    0.05       0
Bank Sta=4995.1,4999.1
Exp/Cntr=0.3,0.1

Type RM Length L Ch R = 1,41689,298,298,298
BEGIN DESCRIPTION:
Mapping XS 384724fd
END DESCRIPTION:
XS GIS Cut Line= 2
      1582725.68      6918144.27      1582079.92      6918008.87
#Sta/Elev= 30
  4675.4 1690.94  4678.3 1690.94  4696.5 1689.13  4706.7 1688.62  4731.3 1686.63
  4747.6 1686.59  4768.1 1687.15  4776.1 1687.12  4808.9 1686.27  4831.1 1686.16
  4860.0 1685.15  4890.7 1684.93  4920.7 1685.54  4990.8 1684.70  4991.1 1684.20
  4994.6 1684.20  4994.8 1684.70  5020.5 1685.02  5025.7 1684.81  5043.9 1685.17
  5054.1 1685.02  5125.7 1686.41  5187.0 1686.53  5215.1 1686.02  5238.1 1685.97
  5265.0 1687.07  5270.1 1686.93  5289.1 1688.23  5314.9 1689.19  5335.2 1689.23
#Mann=3,-1,0
  4675.4    0.05       0  4990.8    0.05       0  4994.8    0.05       0
Bank Sta=4990.8,4994.8
Exp/Cntr=0.3,0.1

Type RM Length L Ch R = 1,41391,202,202,202
BEGIN DESCRIPTION:
Mapping XS ba7829e6
END DESCRIPTION:
XS GIS Cut Line= 4
      1582843.82      6917644.27      1582284.76      6917883.00
      1582195.19      6917859.58      1581972.29      6917883.86
#Sta/Elev= 30
  4555.9 1693.18  4558.0 1693.18  4565.5 1691.38  4574.5 1689.89  4580.0 1690.02
  4587.2 1688.09  4603.6 1685.05  4630.6 1683.95  4630.9 1683.45  4634.4 1683.45
  4634.6 1683.95  4656.2 1683.98  4703.4 1685.22  4785.1 1685.06  4837.8 1685.80
  4855.9 1685.50  4861.4 1685.03  4914.0 1684.29  4932.2 1684.84  4978.7 1684.19
  5037.5 1684.05  5054.8 1684.87  5113.7 1685.21  5137.4 1684.90  5194.6 1685.46
  5247.1 1685.16  5357.2 1687.07  5381.3 1685.87  5397.4 1685.96  5480.6 1687.83
#Mann=3,-1,0
  4555.9    0.05       0  4630.6    0.05       0  4634.6    0.05       0
Bank Sta=4630.6,4634.6
Exp/Cntr=0.3,0.1

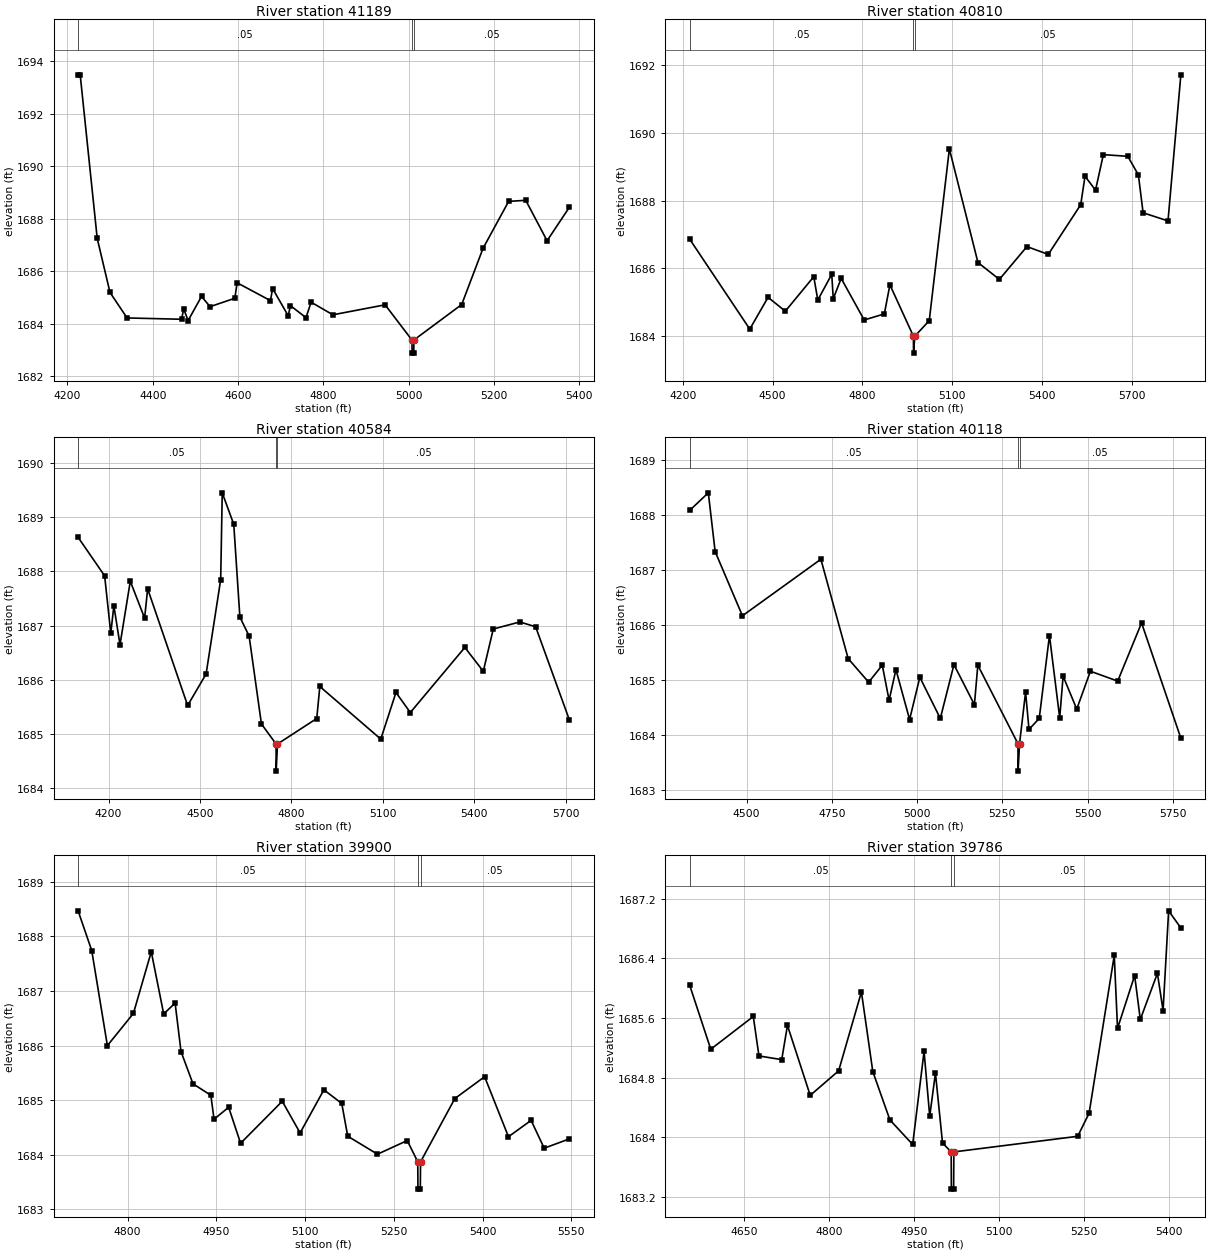
Type RM Length L Ch R = 1,41189,379,379,379
BEGIN DESCRIPTION:
Mapping XS b8b5cde0
END DESCRIPTION:
XS GIS Cut Line= 5
      1582849.77      6917625.66      1582702.82      6917625.66
      1582304.51      6917528.45      1582242.86      6917836.66
      1581963.10      6917822.44
#Sta/Elev= 30
  4225.1 1693.48  4230.0 1693.48  4269.9 1687.25  4299.9 1685.19  4339.9 1684.22
  4467.6 1684.17  4472.7 1684.56  4483.0 1684.12  4514.4 1685.04  4534.5 1684.65
  4592.6 1684.97  4597.8 1685.56  4676.0 1684.88  4681.1 1685.34  4717.7 1684.30
  4722.8 1684.69  4759.3 1684.23  4771.3 1684.82  4822.4 1684.34  4944.8 1684.72
  5007.7 1683.38  5008.1 1682.88  5012.0 1682.88  5012.3 1683.38  5124.3 1684.73
  5174.3 1686.87  5234.4 1688.66  5274.5 1688.70  5324.5 1687.16  5376.5 1688.43
#Mann=3,-1,0
  4225.1    0.05       0  5007.7    0.05       0  5012.3    0.05       0
Bank Sta=5007.7,5012.3
Exp/Cntr=0.3,0.1

Type RM Length L Ch R = 1,40810,226,226,226
BEGIN DESCRIPTION:
Mapping XS 966bc62a
END DESCRIPTION:
XS GIS Cut Line= 4
      1582942.25      6917514.22      1582306.88      6917390.94
      1582086.84      6917424.66      1581331.64      6917263.21
#Sta/Elev= 30
  4222.9 1686.86  4423.8 1684.20  4484.9 1685.14  4542.6 1684.73  4637.7 1685.75
  4651.2 1685.06  4697.8 1685.82  4702.9 1685.10  4729.4 1685.70  4806.3 1684.47
  4873.6 1684.65  4892.3 1685.51  4970.9 1683.99  4971.2 1683.49  4975.5 1683.99
  5023.8 1684.45  5091.1 1689.53  5186.6 1686.17  5258.2 1685.67  5350.3 1686.64
  5421.8 1686.41  5530.2 1687.88  5544.6 1688.72  5579.7 1688.31  5605.9 1689.36
  5687.7 1689.31  5723.0 1688.76  5738.8 1687.64  5822.0 1687.40  5865.0 1691.72
#Mann=3,-1,0
  4222.9    0.05       0  4970.9    0.03       0  4975.5    0.05       0
Bank Sta=4970.9,4975.5
Exp/Cntr=0.3,0.1

Type RM Length L Ch R = 1,40584,466,466,466
BEGIN DESCRIPTION:
Mapping XS 591307d7
END DESCRIPTION:
XS GIS Cut Line= 4
      1582911.32      6917130.42      1581909.62      6917264.83
      1581599.86      6917148.62      1581338.46      6917078.74
#Sta/Elev= 30
  4099.9 1688.63  4187.0 1687.92  4207.2 1686.86  4217.3 1687.37  4237.4 1686.65
  4271.2 1687.82  4318.2 1687.14  4328.2 1687.68  4459.4 1685.53  4520.0 1686.11
  4567.9 1687.85  4573.0 1689.45  4610.8 1688.87  4630.9 1687.16  4661.2 1686.81
  4701.6 1685.19  4749.7 1684.82  4750.0 1684.32  4754.3 1684.82  4883.2 1685.29
  4893.3 1685.88  5093.4 1684.91  5143.2 1685.77  5190.3 1685.40  5369.3 1686.60
  5429.8 1686.16  5462.6 1686.94  5550.0 1687.07  5601.7 1686.98  5712.0 1685.27
#Mann=3,-1,0
  4099.9    0.05       0  4749.7    0.03       0  4754.3    0.05       0
Bank Sta=4749.7,4754.3
Exp/Cntr=0.3,0.1

Type RM Length L Ch R = 1,40118,218,218,218
BEGIN DESCRIPTION:
Mapping XS 75dcfb2b
END DESCRIPTION:
XS GIS Cut Line= 2
      1582659.57      6916839.62      1581219.86      6916863.44
#Sta/Elev= 30
  4333.4 1688.09  4388.0 1688.41  4408.0 1687.34  4488.0 1686.17  4718.0 1687.20
  4798.0 1685.39  4858.0 1684.96  4898.0 1685.27  4918.0 1684.63  4938.0 1685.19
  4978.1 1684.28  5008.1 1685.05  5068.1 1684.30  5108.1 1685.28  5168.1 1684.55
  5178.1 1685.27  5295.7 1683.84  5296.1 1683.34  5300.4 1683.84  5318.1 1684.78
  5328.1 1684.10  5358.1 1684.30  5388.1 1685.81  5418.1 1684.31  5428.1 1685.07
  5468.1 1684.47  5508.1 1685.16  5588.1 1684.98  5658.1 1686.04  5773.3 1683.94
#Mann=3,-1,0
  4333.4    0.05       0  5295.7    0.03       0  5300.4    0.05       0
Bank Sta=5295.7,5300.4
Exp/Cntr=0.3,0.1

Type RM Length L Ch R = 1,39900,114,114,114
BEGIN DESCRIPTION:
Mapping XS 32418681
END DESCRIPTION:
XS GIS Cut Line= 2
      1582287.96      6916698.64      1581462.83      6916606.17
#Sta/Elev= 30
  4716.3 1688.47  4739.4 1687.74  4765.8 1686.00  4809.8 1686.59  4840.0 1687.72
  4861.0 1686.58  4880.3 1686.78  4890.3 1685.89  4910.5 1685.30  4940.7 1685.09
  4946.1 1684.65  4970.8 1684.87  4991.0 1684.21  5061.4 1684.98  5091.6 1684.40
  5131.8 1685.19  5162.0 1684.94  5172.1 1684.34  5222.4 1684.01  5272.7 1684.26
  5290.5 1683.87  5290.8 1683.37  5294.8 1683.37  5295.2 1683.87  5353.2 1685.03
  5403.5 1685.43  5443.8 1684.33  5482.1 1684.63  5504.2 1684.12  5546.6 1684.29
#Mann=3,-1,0
  4716.3    0.05       0  5290.5    0.03       0  5295.2    0.05       0
Bank Sta=5290.5,5295.2
Exp/Cntr=0.3,0.1

Type RM Length L Ch R = 1,39786,264,264,264
BEGIN DESCRIPTION:
Mapping XS 58646f16
END DESCRIPTION:
XS GIS Cut Line= 2
      1582446.75      6916596.69      1581583.76      6916511.34
#Sta/Elev= 30
  4554.4 1686.04  4591.6 1685.18  4666.7 1685.62  4676.7 1685.09  4716.9 1685.04
  4727.0 1685.50  4767.2 1684.56  4817.4 1684.89  4857.6 1685.95  4877.7 1684.88
  4907.9 1684.23  4948.1 1683.90  4968.2 1685.15  4978.2 1684.28  4988.3 1684.86
  5000.8 1683.92  5016.1 1683.80  5016.4 1683.30  5020.4 1683.30  5020.8 1683.80
  5239.5 1684.01  5259.6 1684.32  5304.0 1686.44  5309.8 1685.46  5340.0 1686.17
  5350.0 1685.58  5380.2 1686.20  5390.2 1685.70  5400.0 1687.04  5421.6 1686.81
#Mann=3,-1,0
  4554.4    0.05       0  5016.1    0.03       0  5020.8    0.05       0
Bank Sta=5016.1,5020.8
Exp/Cntr=0.3,0.1

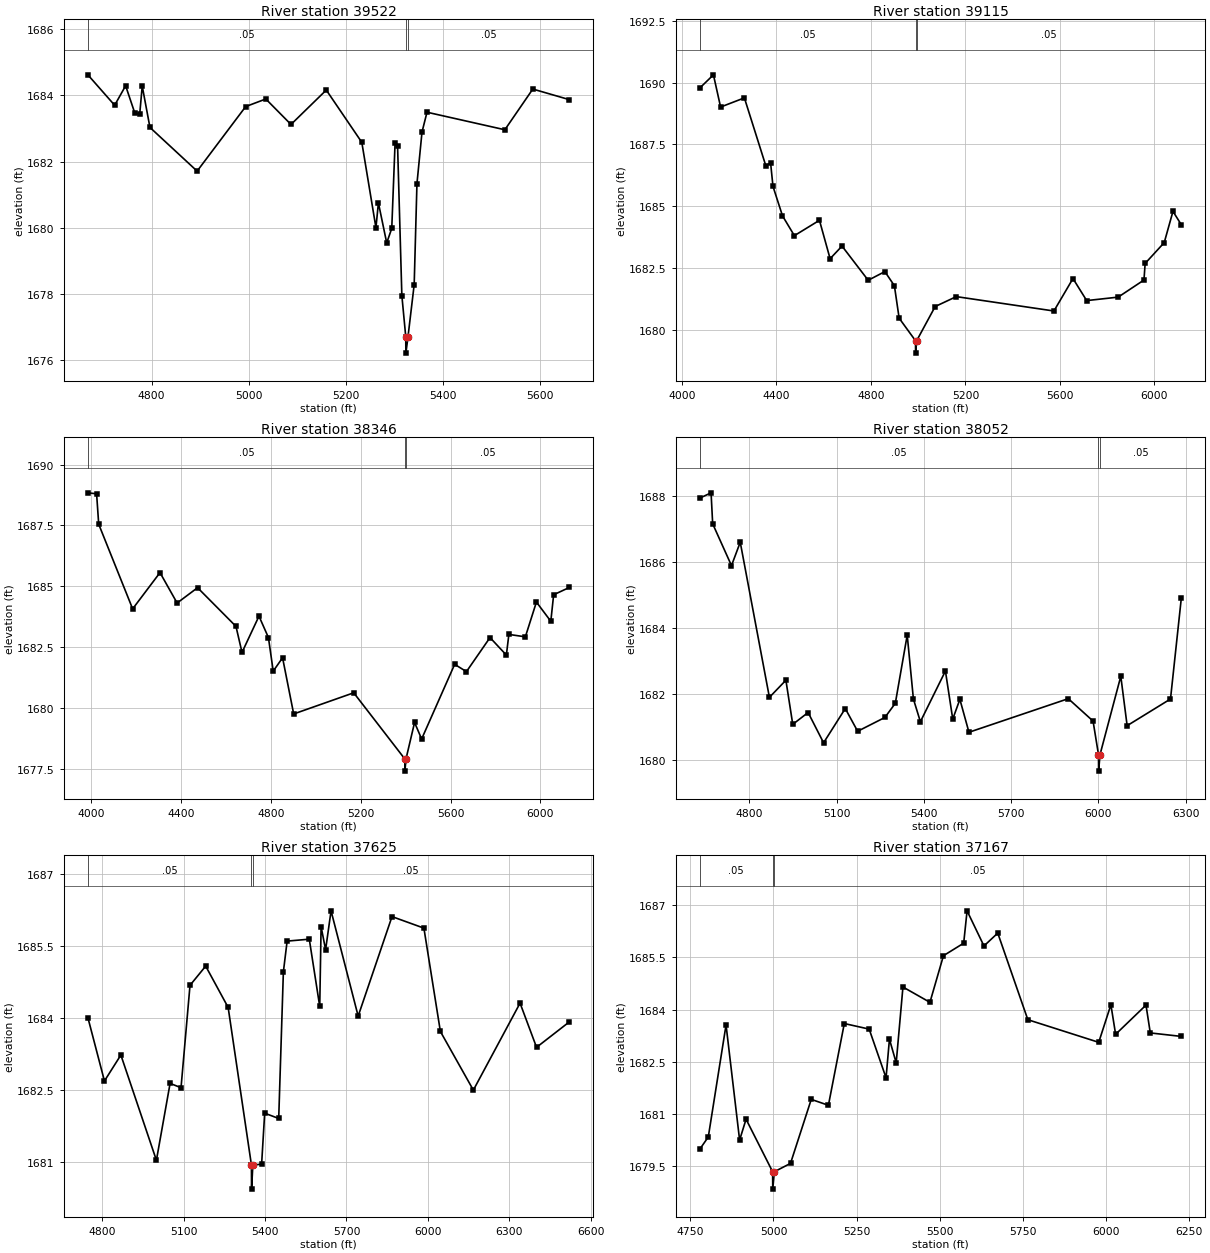
Type RM Length L Ch R = 1,39522,407,407,407
BEGIN DESCRIPTION:
Mapping XS fa6a5149
END DESCRIPTION:
XS GIS Cut Line= 2
      1582308.23      6916442.90      1581352.46      6916177.27
#Sta/Elev= 30
  4668.8 1684.62  4724.0 1683.70  4746.6 1684.29  4765.6 1683.46  4775.6 1683.43
  4780.8 1684.28  4796.7 1683.03  4893.9 1681.71  4993.9 1683.66  5035.4 1683.89
  5087.3 1683.12  5160.0 1684.16  5233.2 1682.58  5262.3 1680.00  5267.4 1680.75
  5284.5 1679.54  5294.9 1679.98  5301.7 1682.55  5306.9 1682.47  5315.7 1677.95
  5323.7 1676.71  5324.0 1676.21  5328.4 1676.71  5341.1 1678.28  5346.8 1681.33
  5357.2 1682.89  5367.5 1683.49  5527.9 1682.96  5585.5 1684.19  5660.8 1683.87
#Mann=3,-1,0
  4668.8    0.05       0  5323.7    0.03       0  5328.4    0.05       0
Bank Sta=5323.7,5328.4
Exp/Cntr=0.3,0.1

Type RM Length L Ch R = 1,39115,769,769,769
BEGIN DESCRIPTION:
Mapping XS 383875e1
END DESCRIPTION:
XS GIS Cut Line= 2
      1582972.08      6916175.55      1580949.79      6915923.85
#Sta/Elev= 30
  4076.0 1689.78  4133.5 1690.31  4163.8 1689.01  4264.5 1689.38  4355.2 1686.64
  4375.4 1686.76  4385.5 1685.81  4425.8 1684.62  4476.1 1683.82  4582.2 1684.44
  4627.3 1682.89  4677.7 1683.40  4788.5 1682.02  4859.1 1682.37  4899.4 1681.80
  4919.5 1680.49  4988.8 1679.58  4989.1 1679.08  4993.6 1679.58  5072.0 1680.96
  5161.4 1681.36  5574.6 1680.78  5655.2 1682.09  5713.3 1681.20  5846.6 1681.34
  5955.7 1682.03  5960.7 1682.70  6041.5 1683.54  6078.4 1684.80  6113.9 1684.26
#Mann=3,-1,0
  4076.0    0.05       0  4988.8    0.03       0  4993.6    0.05       0
Bank Sta=4988.8,4993.6
Exp/Cntr=0.3,0.1

Type RM Length L Ch R = 1,38346,294,294,294
BEGIN DESCRIPTION:
Mapping XS 34242ddc
END DESCRIPTION:
XS GIS Cut Line= 2
      1582880.95      6915793.61      1580838.35      6915138.76
#Sta/Elev= 30
  3984.0 1688.84  4022.9 1688.80  4032.3 1687.55  4183.5 1684.07  4305.3 1685.56
  4381.6 1684.31  4472.7 1684.94  4643.8 1683.35  4670.7 1682.28  4746.3 1683.77
  4788.4 1682.89  4809.7 1681.51  4851.4 1682.06  4900.9 1679.75  5168.4 1680.62
  5396.0 1677.90  5396.4 1677.40  5401.2 1677.90  5439.4 1679.40  5470.9 1678.72
  5618.0 1681.79  5670.5 1681.49  5775.5 1682.89  5848.4 1682.17  5859.5 1683.02
  5933.0 1682.92  5982.2 1684.35  6046.4 1683.56  6059.0 1684.65  6129.0 1684.95
#Mann=3,-1,0
  3984.0    0.05       0  5396.0    0.03       0  5401.2    0.05       0
Bank Sta=5396,5401.2
Exp/Cntr=0.3,0.1

Type RM Length L Ch R = 1,38052,427,427,427
BEGIN DESCRIPTION:
Mapping XS 943e160b
END DESCRIPTION:
XS GIS Cut Line= 3
      1582503.47      6915346.54      1582177.56      6915320.66
      1580929.99      6914863.00
#Sta/Elev= 30
  4629.6 1687.94  4668.2 1688.10  4673.7 1687.16  4738.4 1685.89  4768.5 1686.60
  4868.8 1681.89  4925.5 1682.41  4949.1 1681.07  5001.9 1681.43  5055.1 1680.51
  5129.7 1681.55  5172.3 1680.86  5266.0 1681.28  5301.8 1681.71  5342.7 1683.78
  5364.0 1681.84  5388.0 1681.15  5474.1 1682.69  5499.3 1681.23  5523.8 1681.83
  5555.0 1680.83  5896.6 1681.85  5981.8 1681.17  6000.5 1680.15  6000.9 1679.65
  6005.7 1680.15  6077.2 1682.53  6099.0 1681.03  6248.1 1681.84  6285.4 1684.91
#Mann=3,-1,0
  4629.6    0.05       0  6000.5    0.05       0  6005.7    0.05       0
Bank Sta=6000.5,6005.7
Exp/Cntr=0.3,0.1

Type RM Length L Ch R = 1,37625,458,458,458
BEGIN DESCRIPTION:
Mapping XS f53f9df9
END DESCRIPTION:
XS GIS Cut Line= 5
      1582555.61      6914966.33      1582133.42      6915019.40
      1581822.52      6914936.56      1581839.02      6914693.06
      1581065.57      6914570.66
#Sta/Elev= 30
  4746.9 1684.01  4808.0 1682.69  4868.5 1683.23  4999.5 1681.04  5049.9 1682.64
  5090.2 1682.55  5123.3 1684.68  5181.1 1685.08  5263.9 1684.22  5349.7 1680.94
  5350.1 1680.44  5354.9 1680.94  5387.2 1680.96  5398.5 1682.02  5450.2 1681.91
  5467.4 1684.96  5481.2 1685.60  5562.9 1685.64  5601.4 1684.24  5606.4 1685.90
  5623.0 1685.42  5643.1 1686.23  5743.0 1684.04  5867.7 1686.11  5985.3 1685.87
  6046.0 1683.72  6167.5 1682.50  6339.6 1684.31  6400.4 1683.39  6521.3 1683.92
#Mann=3,-1,0
  4746.9    0.05       0  5349.7    0.05       0  5354.9    0.05       0
Bank Sta=5349.7,5354.9
Exp/Cntr=0.3,0.1

Type RM Length L Ch R = 1,37167,436,436,436
BEGIN DESCRIPTION:
Mapping XS 9f8527d8
END DESCRIPTION:
XS GIS Cut Line= 3
      1582469.65      6914604.35      1582047.34      6914712.22
      1581050.30      6914536.39
#Sta/Elev= 30
  4778.6 1679.99  4804.0 1680.34  4857.4 1683.56  4898.2 1680.25  4917.6 1680.85
  4997.5 1679.34  4997.9 1678.84  5002.7 1679.34  5051.3 1679.58  5113.7 1681.42
  5165.3 1681.25  5213.1 1683.60  5287.9 1683.44  5338.7 1682.04  5348.9 1683.15
  5369.2 1682.47  5389.5 1684.65  5470.7 1684.21  5511.3 1685.55  5572.2 1685.91
  5582.4 1686.84  5633.2 1685.83  5674.7 1686.20  5765.2 1683.71  5978.4 1683.06
  6015.0 1684.14  6029.2 1683.29  6120.6 1684.13  6133.5 1683.33  6226.9 1683.23
#Mann=3,-1,0
  4778.6    0.05       0  4997.5    0.05       0  5002.7    0.05       0
Bank Sta=4997.5,5002.7
Exp/Cntr=0.3,0.1

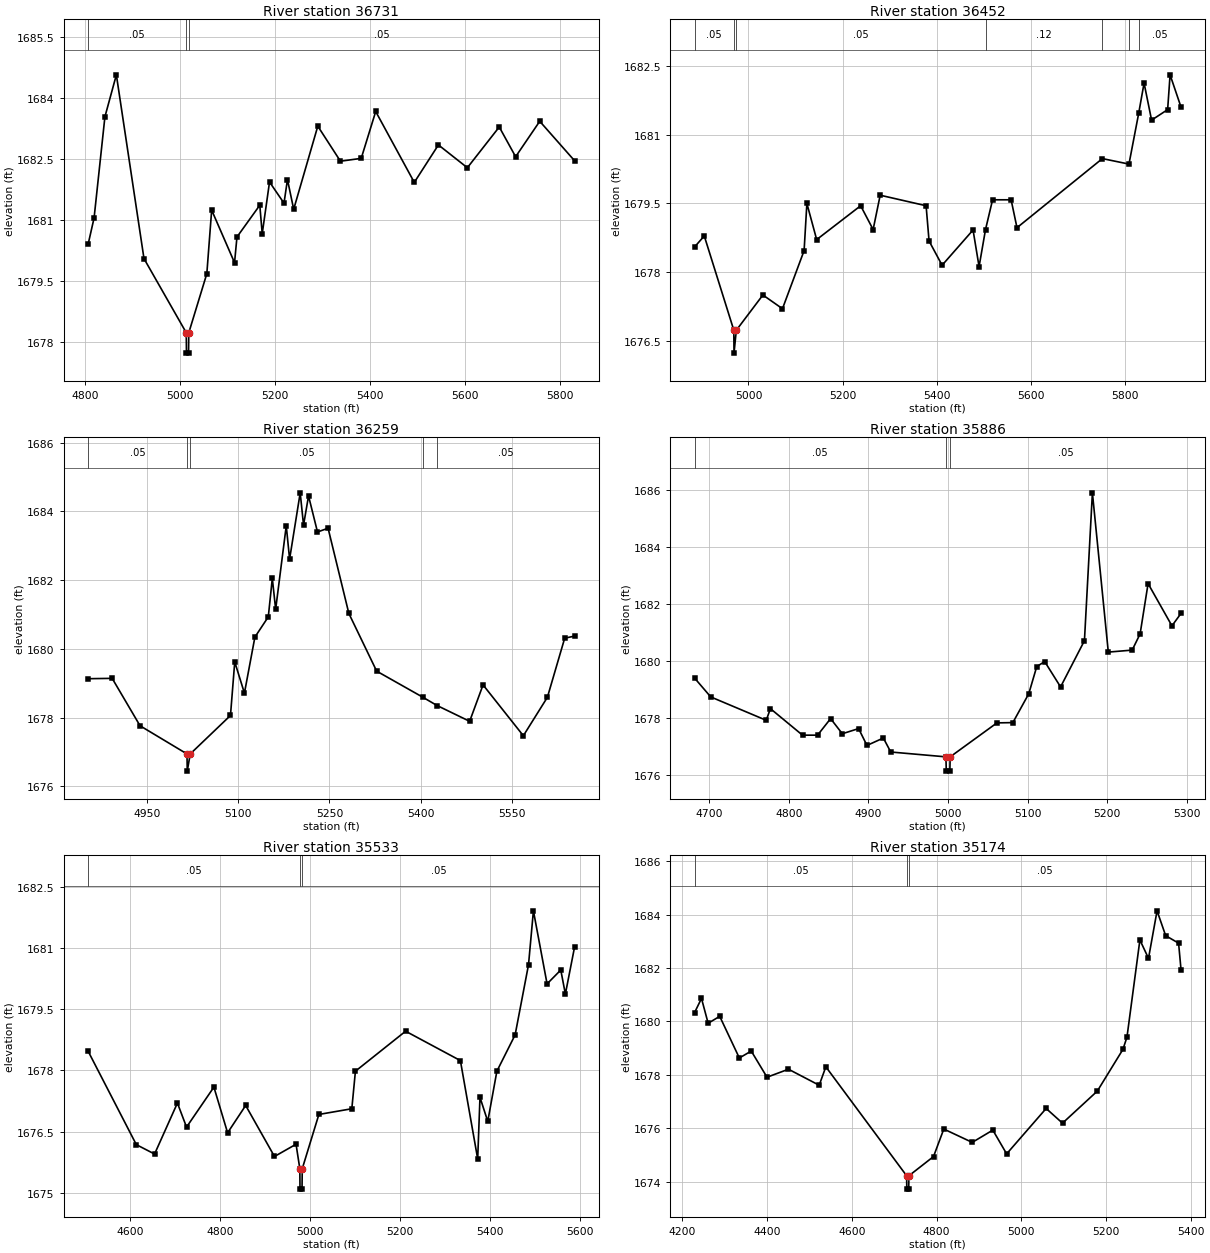
Type RM Length L Ch R = 1,36731,279,279,279
BEGIN DESCRIPTION:
Mapping XS 6b096c16
END DESCRIPTION:
XS GIS Cut Line= 3
      1582289.36      6914299.34      1582154.41      6914332.06
      1581282.70      6914491.33
#Sta/Elev= 30
  4805.7 1680.40  4818.3 1681.05  4841.1 1683.53  4865.2 1684.56  4923.4 1680.05
  5012.5 1678.23  5012.9 1677.73  5017.3 1677.73  5017.8 1678.23  5055.8 1679.68
  5066.0 1681.24  5114.2 1679.95  5119.3 1680.58  5167.4 1681.36  5172.5 1680.66
  5187.9 1681.93  5218.4 1681.41  5225.7 1681.99  5238.8 1681.26  5289.6 1683.30
  5337.3 1682.44  5381.1 1682.51  5411.6 1683.66  5492.9 1681.92  5543.7 1682.84
  5604.7 1682.28  5671.9 1683.28  5706.4 1682.55  5757.2 1683.42  5830.7 1682.45
#Mann=3,-1,0
  4805.7    0.05       0  5012.5    0.03       0  5017.8    0.05       0
Bank Sta=5012.5,5017.8
Exp/Cntr=0.3,0.1

Type RM Length L Ch R = 1,36452,193,193,193
BEGIN DESCRIPTION:
Mapping XS 2655c1d3
END DESCRIPTION:
XS GIS Cut Line= 2
      1582264.82      6914135.73      1581269.23      6913856.17
#Sta/Elev= 30
  4885.4 1678.55  4906.0 1678.79  4968.8 1676.73  4969.2 1676.23  4974.1 1676.73
  5030.6 1677.50  5072.2 1677.20  5118.2 1678.47  5124.1 1679.50  5144.9 1678.71
  5238.4 1679.45  5264.9 1678.93  5279.9 1679.68  5377.5 1679.45  5383.8 1678.68
  5411.5 1678.15  5477.3 1678.92  5490.1 1678.12  5503.8 1678.93  5518.8 1679.58
  5558.2 1679.58  5570.7 1678.97  5752.2 1680.48  5808.7 1680.36  5829.4 1681.47
  5840.8 1682.13  5856.8 1681.32  5890.9 1681.55  5896.1 1682.31  5919.5 1681.60
#Mann=7,-1,0
  4885.4    0.05       0  4968.8    0.03       0  4974.1    0.05       0
  5503.8    0.12       0  5752.2    0.05       0  5808.7    0.12       0
  5829.4    0.05       0
Bank Sta=4968.8,4974.1
Exp/Cntr=0.3,0.1

Type RM Length L Ch R = 1,36259,373,373,373
BEGIN DESCRIPTION:
Mapping XS 45ac5d30
END DESCRIPTION:
XS GIS Cut Line= 2
      1582293.43      6914000.75      1581568.60      6913664.57
#Sta/Elev= 30
  4853.6 1679.13  4893.1 1679.14  4938.9 1677.76  5016.0 1676.94  5016.4 1676.44
  5021.3 1676.94  5087.4 1678.06  5094.4 1679.62  5110.3 1678.71  5127.5 1680.34
  5149.5 1680.93  5156.1 1682.05  5161.6 1681.15  5179.0 1683.58  5184.5 1682.61
  5201.9 1684.54  5207.4 1683.60  5215.6 1684.45  5230.3 1683.40  5247.7 1683.51
  5281.8 1681.03  5327.5 1679.35  5403.4 1678.59  5426.6 1678.35  5480.2 1677.89
  5502.2 1678.95  5568.4 1677.47  5607.9 1678.59  5636.3 1680.31  5652.6 1680.37
#Mann=5,-1,0
  4853.6    0.05       0  5016.0    0.05       0  5021.3    0.05       0
  5403.4    0.12       0  5426.6    0.05       0
Bank Sta=5016,5021.3
Exp/Cntr=0.3,0.1

Type RM Length L Ch R = 1,35886,353,353,353
BEGIN DESCRIPTION:
Mapping XS 48bc21c7
END DESCRIPTION:
XS GIS Cut Line= 3
      1582293.47      6913947.61      1582211.84      6913635.60
      1582211.84      6913346.52
#Sta/Elev= 30
  4681.4 1679.41  4701.7 1678.75  4771.5 1677.93  4776.7 1678.34  4817.1 1677.41
  4836.0 1677.41  4852.4 1677.99  4867.1 1677.46  4887.6 1677.64  4898.1 1677.05
  4918.7 1677.31  4928.0 1676.82  4997.4 1676.65  4997.8 1676.15  5002.3 1676.15
  5002.7 1676.65  5061.5 1677.84  5081.5 1677.85  5101.5 1678.86  5111.5 1679.81
  5121.5 1679.99  5141.5 1679.10  5171.5 1680.72  5181.5 1685.90  5201.5 1680.32
  5231.5 1680.39  5241.5 1680.96  5251.5 1682.72  5281.5 1681.24  5293.0 1681.68
#Mann=3,-1,0
  4681.4    0.05       0  4997.4    0.03       0  5002.7    0.05       0
Bank Sta=4997.4,5002.7
Exp/Cntr=0.3,0.1

Type RM Length L Ch R = 1,35533,359,359,359
BEGIN DESCRIPTION:
Mapping XS 588d15c4
END DESCRIPTION:
XS GIS Cut Line= 2
      1582357.90      6914363.60      1582547.18      6913297.67
#Sta/Elev= 30
  4505.9 1678.47  4613.2 1676.18  4653.8 1675.95  4704.6 1677.20  4724.9 1676.61
  4785.8 1677.59  4816.3 1676.47  4856.5 1677.14  4920.6 1675.89  4968.6 1676.19
  4977.0 1675.59  4977.4 1675.09  4981.9 1675.09  4982.4 1675.59  5019.4 1676.92
  5092.7 1677.06  5100.7 1677.98  5212.4 1678.96  5334.3 1678.24  5372.8 1675.83
  5377.9 1677.34  5395.2 1676.75  5415.5 1677.98  5456.1 1678.87  5485.9 1680.59
  5496.8 1681.91  5527.2 1680.12  5557.7 1680.46  5567.9 1679.87  5588.5 1681.03
#Mann=3,-1,0
  4505.9    0.05       0  4977.0    0.05       0  4982.4    0.05       0
Bank Sta=4977,4982.4
Exp/Cntr=0.3,0.1

Type RM Length L Ch R = 1,35174,421,421,421
BEGIN DESCRIPTION:
Mapping XS 4684b5e6
END DESCRIPTION:
XS GIS Cut Line= 3
      1582816.98      6914749.21      1582632.94      6914434.31
      1582763.68      6913662.14
#Sta/Elev= 30
  4228.9 1680.33  4245.2 1680.86  4260.9 1679.93  4288.2 1680.19  4334.5 1678.63
  4362.6 1678.89  4399.8 1677.91  4450.4 1678.21  4522.9 1677.61  4538.6 1678.30
  4729.2 1674.22  4729.6 1673.72  4734.1 1673.72  4734.6 1674.22  4792.7 1674.94
  4816.9 1675.97  4884.0 1675.47  4932.6 1675.93  4965.2 1675.04  5058.4 1676.74
  5097.0 1676.19  5179.1 1677.39  5239.5 1678.95  5249.1 1679.41  5279.6 1683.05
  5299.9 1682.36  5320.1 1684.14  5340.4 1683.21  5370.9 1682.93  5376.8 1681.91
#Mann=3,-1,0
  4228.9    0.05       0  4729.2    0.05       0  4734.6    0.05       0
Bank Sta=4729.2,4734.6
Exp/Cntr=0.3,0.1

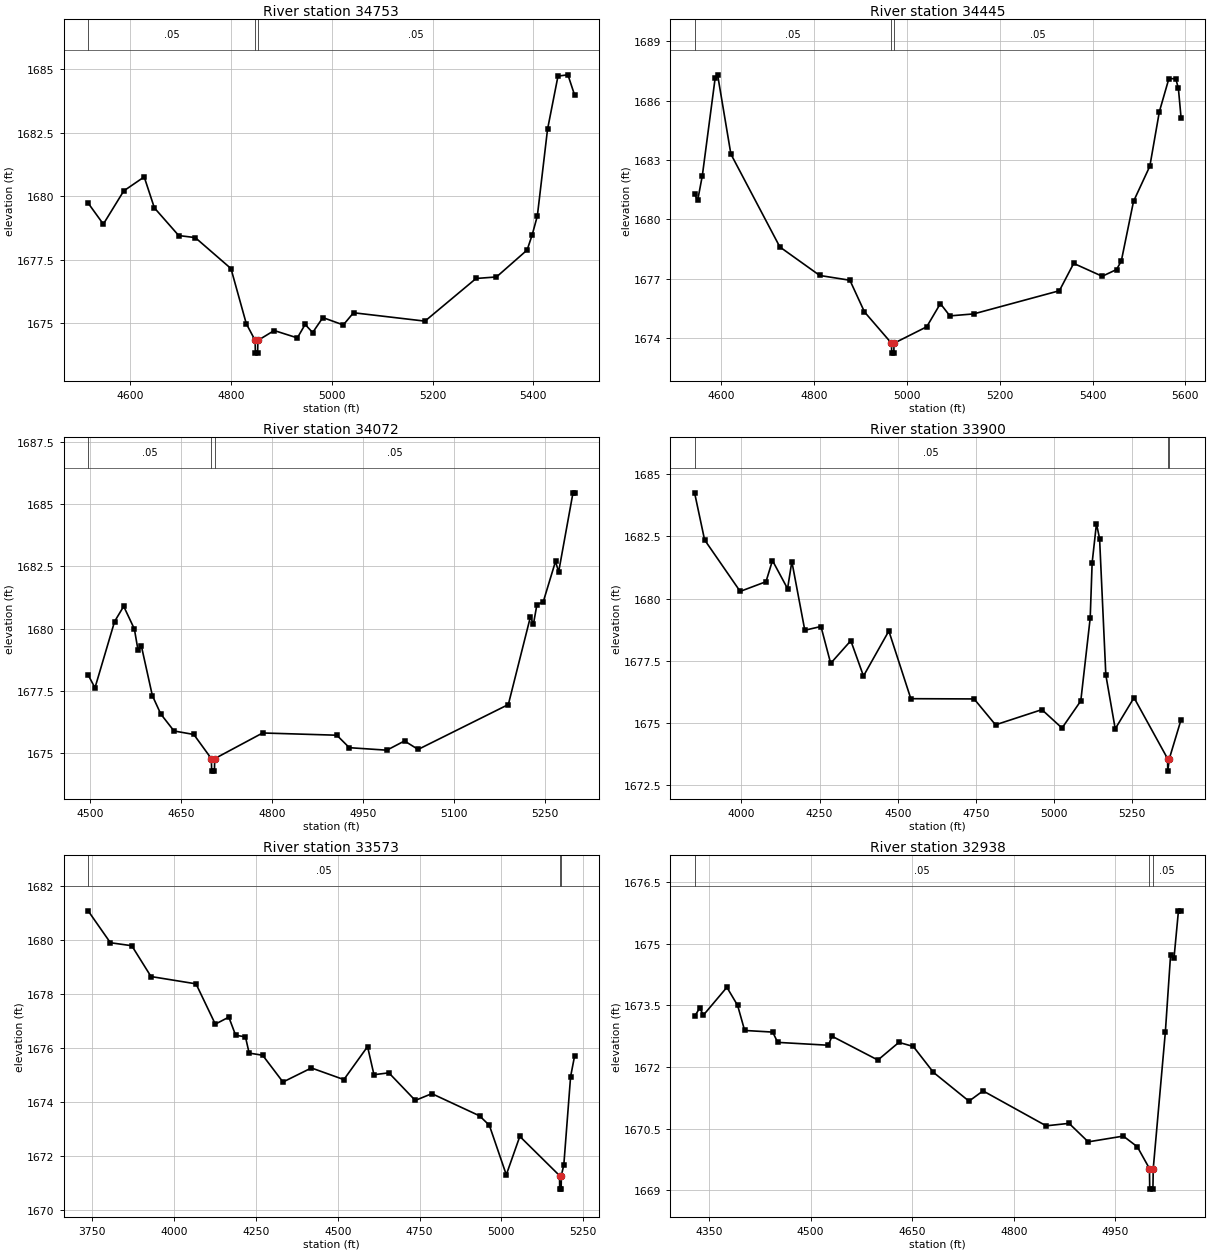
Type RM Length L Ch R = 1,34753,308,308,308
BEGIN DESCRIPTION:
Mapping XS 0427b54d
END DESCRIPTION:
XS GIS Cut Line= 2
      1582890.62      6914777.83      1583046.03      6913824.92
#Sta/Elev= 30
  4516.3 1679.73  4546.5 1678.90  4587.1 1680.21  4627.6 1680.76  4647.8 1679.54
  4696.1 1678.45  4728.9 1678.37  4799.8 1677.15  4830.2 1674.98  4847.8 1674.32
  4848.2 1673.82  4852.7 1673.82  4853.2 1674.32  4885.6 1674.71  4931.5 1674.42
  4947.0 1674.95  4961.9 1674.63  4982.2 1675.22  5022.7 1674.93  5043.0 1675.41
  5184.8 1675.08  5286.2 1676.76  5326.7 1676.82  5387.5 1677.88  5397.6 1678.48
  5407.8 1679.22  5428.0 1682.63  5448.8 1684.73  5468.5 1684.78  5481.8 1683.98
#Mann=3,-1,0
  4516.3    0.05       0  4847.8    0.05       0  4853.2    0.05       0
Bank Sta=4847.8,4853.2
Exp/Cntr=0.3,0.1

Type RM Length L Ch R = 1,34445,373,373,373
BEGIN DESCRIPTION:
Mapping XS c207101d
END DESCRIPTION:
XS GIS Cut Line= 2
      1583119.65      6914884.25      1583352.64      6913862.38
#Sta/Elev= 30
  4542.7 1681.28  4549.3 1680.96  4559.4 1682.21  4587.1 1687.15  4592.3 1687.30
  4620.9 1683.30  4726.4 1678.61  4812.4 1677.17  4877.3 1676.93  4908.7 1675.33
  4966.9 1673.75  4967.3 1673.25  4971.9 1673.25  4972.4 1673.75  5042.8 1674.58
  5072.2 1675.75  5092.7 1675.13  5144.0 1675.23  5328.6 1676.40  5359.4 1677.78
  5420.9 1677.13  5451.7 1677.47  5462.0 1677.90  5488.3 1680.91  5523.5 1682.69
  5544.0 1685.44  5564.5 1687.11  5579.4 1687.10  5585.0 1686.61  5590.8 1685.12
#Mann=3,-1,0
  4542.7    0.05       0  4966.9    0.05       0  4972.4    0.05       0
Bank Sta=4966.9,4972.4
Exp/Cntr=0.3,0.1

Type RM Length L Ch R = 1,34072,172,172,172
BEGIN DESCRIPTION:
Mapping XS 5e4f9cd9
END DESCRIPTION:
XS GIS Cut Line= 3
      1583417.55      6914698.14      1583552.98      6914380.39
      1583443.62      6913937.71
#Sta/Elev= 30
  4497.1 1678.15  4508.4 1677.63  4540.7 1680.29  4555.7 1680.90  4573.3 1679.99
  4579.3 1679.14  4584.8 1679.31  4602.9 1677.32  4616.8 1676.58  4638.6 1675.90
  4671.2 1675.76  4700.1 1674.79  4700.6 1674.29  4705.2 1674.29  4705.6 1674.79
  4784.6 1675.82  4906.8 1675.73  4927.4 1675.23  4989.2 1675.13  5018.3 1675.50
  5040.7 1675.16  5189.3 1676.96  5225.6 1680.47  5230.7 1680.19  5236.4 1680.97
  5246.7 1681.07  5267.0 1682.70  5272.2 1682.28  5295.8 1685.45  5298.5 1685.45
#Mann=3,-1,0
  4497.1    0.05       0  4700.1    0.03       0  4705.6    0.05       0
Bank Sta=4700.1,4705.6
Exp/Cntr=0.3,0.1

Type RM Length L Ch R = 1,33900,327,327,327
BEGIN DESCRIPTION:
Mapping XS 8527691e
END DESCRIPTION:
XS GIS Cut Line= 4
      1583384.40      6915248.92      1583646.73      6914244.98
      1583657.15      6914010.60      1583669.73      6913727.64
#Sta/Elev= 30
  3850.4 1684.25  3882.4 1682.36  3996.2 1680.29  4078.7 1680.68  4099.4 1681.53
  4147.7 1680.40  4161.4 1681.49  4202.8 1678.73  4254.5 1678.88  4285.5 1677.40
  4349.9 1678.31  4390.4 1676.89  4471.5 1678.70  4541.8 1675.98  4744.1 1675.97
  4812.6 1674.93  4960.8 1675.54  5025.2 1674.80  5085.2 1675.89  5115.3 1679.22
  5121.5 1681.44  5135.3 1683.01  5145.3 1682.41  5165.3 1676.93  5195.3 1674.77
  5255.4 1676.02  5362.8 1673.57  5363.2 1673.07  5368.3 1673.57  5405.9 1675.14
#Mann=3,-1,0
  3850.4    0.05       0  5362.8    0.03       0  5368.3    0.05       0
Bank Sta=5362.8,5368.3
Exp/Cntr=0.3,0.1

Type RM Length L Ch R = 1,33573,635,635,635
BEGIN DESCRIPTION:
Mapping XS 8d53fdf0
END DESCRIPTION:
XS GIS Cut Line= 2
      1583586.53      6915163.87      1583965.07      6913726.07
#Sta/Elev= 30
  3737.1 1681.07  3805.2 1679.89  3870.5 1679.78  3929.3 1678.64  4066.9 1678.37
  4125.8 1676.88  4167.1 1677.14  4187.9 1676.47  4217.9 1676.41  4229.2 1675.81
  4270.5 1675.73  4332.6 1674.74  4419.5 1675.26  4518.7 1674.83  4591.1 1676.05
  4610.7 1675.01  4656.2 1675.08  4736.9 1674.06  4787.6 1674.31  4933.3 1673.49
  4963.3 1673.14  5015.1 1671.31  5056.4 1672.73  5177.8 1671.28  5178.2 1670.78
  5182.8 1670.78  5183.3 1671.28  5190.9 1671.68  5211.6 1674.94  5223.9 1675.71
#Mann=3,-1,0
  3737.1    0.05       0  5177.8    0.03       0  5183.3    0.05       0
Bank Sta=5177.8,5183.3
Exp/Cntr=0.3,0.1

Type RM Length L Ch R = 1,32938,527,527,527
BEGIN DESCRIPTION:
Mapping XS d9752a2c
END DESCRIPTION:
XS GIS Cut Line= 2
      1584227.73      6914539.37      1584413.37      6913845.58
#Sta/Elev= 30
  4328.8 1673.23  4336.5 1673.44  4341.7 1673.26  4376.5 1673.94  4392.3 1673.50
  4402.7 1672.89  4444.1 1672.85  4451.5 1672.60  4526.4 1672.53  4531.6 1672.75
  4599.4 1672.17  4630.4 1672.60  4651.7 1672.50  4681.4 1671.87  4733.9 1671.17
  4754.6 1671.42  4847.8 1670.57  4881.6 1670.63  4909.9 1670.18  4961.7 1670.32
  4982.4 1670.06  5000.3 1669.53  5000.7 1669.03  5005.4 1669.03  5005.9 1669.53
  5023.8 1672.86  5031.5 1674.73  5036.6 1674.66  5043.1 1675.80  5047.0 1675.80
#Mann=3,-1,0
  4328.8    0.05       0  5000.3    0.05       0  5005.9    0.05       0
Bank Sta=5000.3,5005.9
Exp/Cntr=0.3,0.1