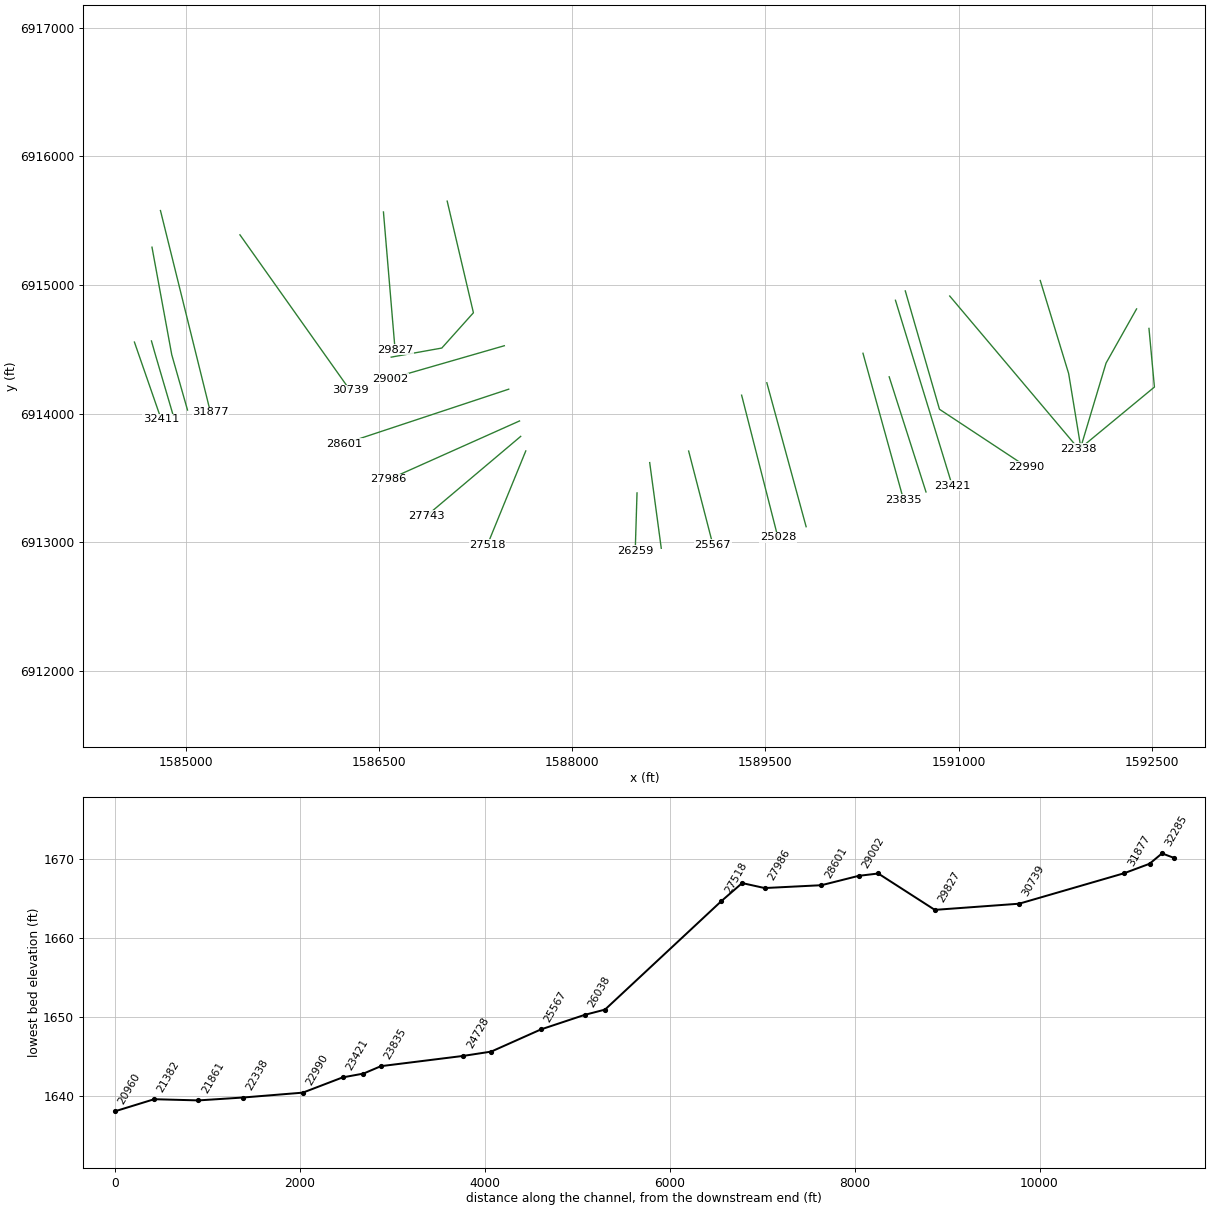
HEC-RAS study Deadman 12.prj: Deadman 12 Base Level Engineering

--- Deadman 12.g01 (geometry) --- (continued)

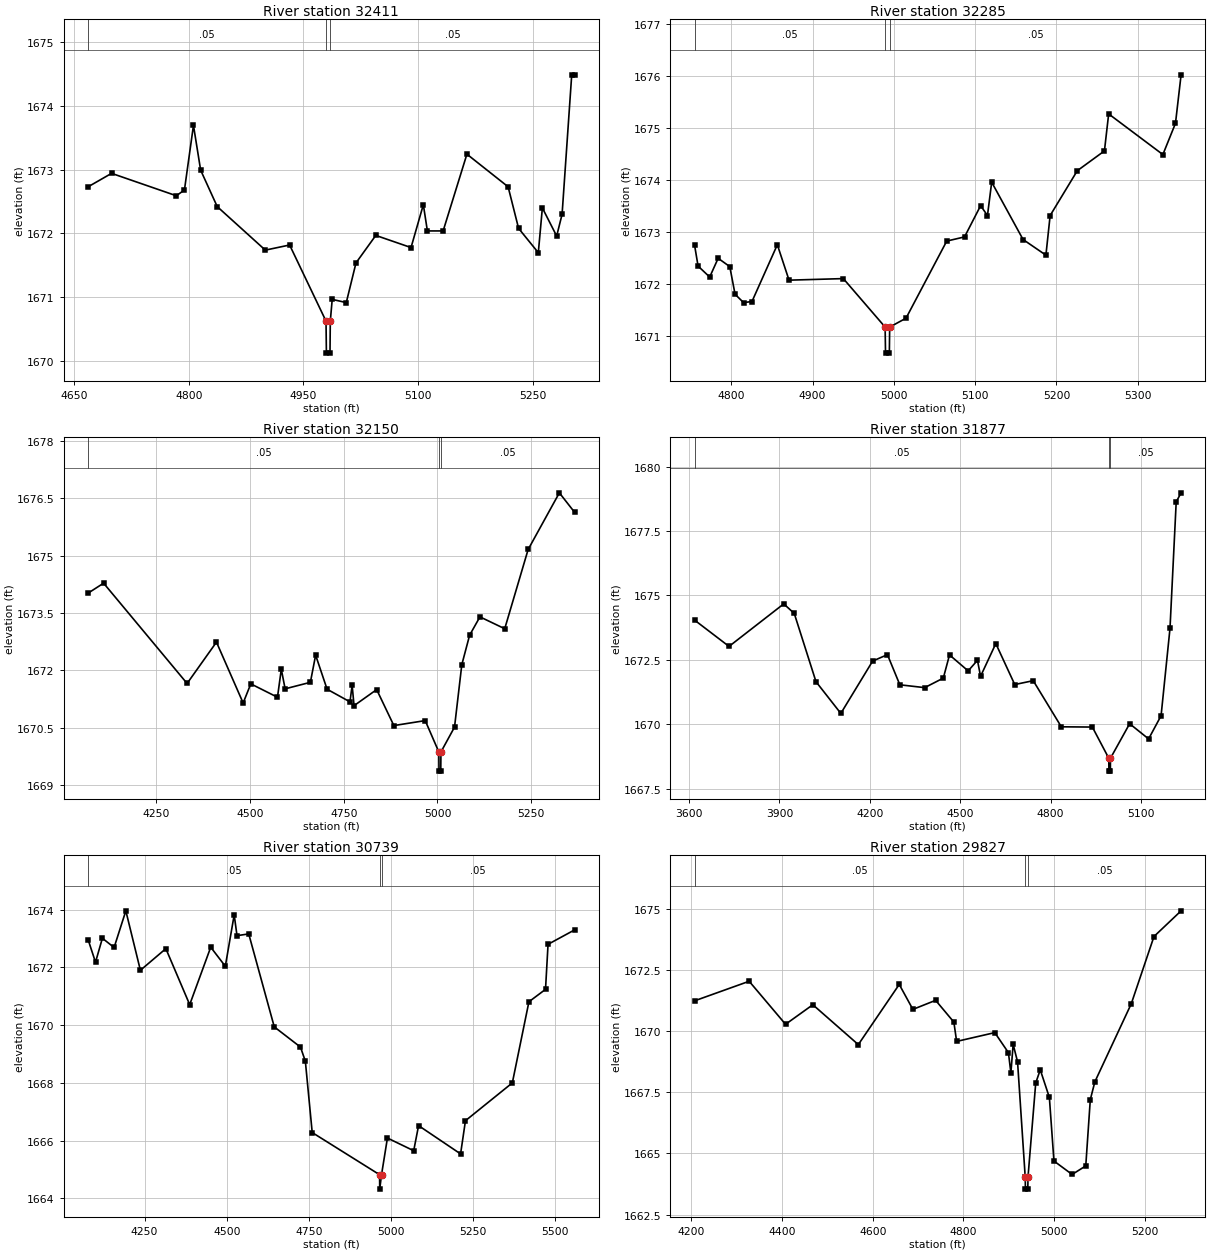
Type RM Length L Ch R = 1,32411,126,126,126
BEGIN DESCRIPTION:
Mapping XS 56c8054c
END DESCRIPTION:
XS GIS Cut Line= 2
      1584596.16      6914557.02      1584804.75      6913955.78
#Sta/Elev= 30
  4668.3 1672.73  4699.0 1672.94  4783.7 1672.59  4794.3 1672.68  4806.1 1673.69
  4815.5 1672.99  4837.2 1672.42  4900.1 1671.74  4931.9 1671.82  4979.5 1670.63
  4980.0 1670.13  4984.7 1670.13  4985.1 1670.63  4987.6 1670.97  5006.0 1670.92
  5018.7 1671.54  5044.6 1671.97  5090.7 1671.78  5106.8 1672.45  5112.1 1672.04
  5132.7 1672.04  5163.8 1673.24  5217.7 1672.73  5231.4 1672.08  5257.2 1671.70
  5262.5 1672.40  5281.2 1671.96  5288.3 1672.30  5300.9 1674.48  5304.7 1674.48
#Mann=3,-1,0
  4668.3    0.05       0  4979.5    0.03       0  4985.1    0.05       0
Bank Sta=4979.5,4985.1
Exp/Cntr=0.3,0.1

Type RM Length L Ch R = 1,32285,135,135,135
BEGIN DESCRIPTION:
Mapping XS 02517062
END DESCRIPTION:
XS GIS Cut Line= 3
      1584728.47      6914565.88      1584761.32      6914450.71
      1584896.26      6913991.38
#Sta/Elev= 30
  4754.9 1672.75  4759.2 1672.35  4773.5 1672.14  4783.9 1672.50  4798.2 1672.34
  4804.7 1671.81  4815.1 1671.65  4825.5 1671.67  4856.7 1672.76  4871.1 1672.08
  4937.9 1672.11  4989.3 1671.18  4989.8 1670.68  4994.5 1670.68  4994.9 1671.18
  5015.0 1671.35  5065.1 1672.83  5087.0 1672.91  5106.8 1673.51  5115.2 1673.32
  5120.4 1673.96  5159.0 1672.86  5187.1 1672.56  5192.3 1673.32  5225.7 1674.18
  5259.1 1674.56  5264.3 1675.27  5331.0 1674.49  5346.5 1675.09  5353.4 1676.02
#Mann=3,-1,0
  4754.9    0.05       0  4989.3    0.03       0  4994.9    0.05       0
Bank Sta=4989.3,4994.9
Exp/Cntr=0.3,0.1

Type RM Length L Ch R = 1,32150,273,273,273
BEGIN DESCRIPTION:
Mapping XS 09515bce
END DESCRIPTION:
XS GIS Cut Line= 3
      1584732.68      6915294.43      1584886.32      6914458.52
      1585008.72      6914028.82
#Sta/Elev= 30
  4068.8 1674.02  4110.1 1674.28  4332.6 1671.66  4410.9 1672.74  4482.0 1671.15
  4502.4 1671.65  4573.5 1671.30  4583.7 1672.03  4593.9 1671.52  4661.2 1671.69
  4675.2 1672.40  4705.7 1671.51  4766.7 1671.18  4772.5 1671.61  4777.6 1671.08
  4837.9 1671.50  4883.7 1670.56  4967.3 1670.69  5003.6 1669.87  5004.0 1669.37
  5008.7 1669.37  5009.2 1669.87  5045.4 1670.52  5064.8 1672.15  5085.6 1672.92
  5113.1 1673.40  5179.2 1673.09  5241.6 1675.16  5324.8 1676.64  5365.5 1676.13
#Mann=3,-1,0
  4068.8    0.05       0  5003.6    0.03       0  5009.2    0.05       0
Bank Sta=5003.6,5009.2
Exp/Cntr=0.3,0.1

Type RM Length L Ch R = 1,31877,1138,1138,1138
BEGIN DESCRIPTION:
Mapping XS 25abb1b2
END DESCRIPTION:
XS GIS Cut Line= 2
      1584798.55      6915578.98      1585186.90      6914012.29
#Sta/Elev= 30
  3618.6 1674.04  3732.9 1673.02  3914.4 1674.67  3949.3 1674.30  4021.4 1671.65
  4103.8 1670.42  4209.3 1672.45  4258.4 1672.70  4299.6 1671.53  4382.0 1671.42
  4443.8 1671.79  4464.4 1672.69  4526.2 1672.07  4557.1 1672.48  4567.4 1671.86
  4618.0 1673.13  4680.8 1671.54  4742.1 1671.69  4835.3 1669.90  4938.3 1669.89
  4992.8 1668.68  4993.3 1668.18  4998.0 1668.18  4998.4 1668.68  5062.0 1670.02
  5124.9 1669.43  5166.3 1670.33  5195.9 1673.72  5216.5 1678.63  5232.7 1678.98
#Mann=3,-1,0
  3618.6    0.05       0  4992.8    0.03       0  4998.4    0.05       0
Bank Sta=4992.8,4998.4
Exp/Cntr=0.3,0.1

Type RM Length L Ch R = 1,30739,912,912,912
BEGIN DESCRIPTION:
Mapping XS 224d7cf0
END DESCRIPTION:
XS GIS Cut Line= 2
      1585416.23      6915390.35      1586272.19      6914182.00
#Sta/Elev= 30
  4078.2 1672.96  4100.7 1672.18  4121.6 1673.01  4157.3 1672.69  4193.0 1673.96
  4237.3 1671.90  4314.8 1672.65  4387.4 1670.71  4451.4 1672.70  4495.8 1672.04
  4522.8 1673.82  4531.4 1673.10  4567.1 1673.16  4644.8 1669.94  4724.6 1669.24
  4739.4 1668.75  4760.3 1666.28  4965.3 1664.82  4965.8 1664.32  4971.3 1664.82
  4989.2 1666.09  5069.2 1665.65  5084.0 1666.52  5211.9 1665.54  5226.7 1666.69
  5369.4 1668.00  5419.9 1670.81  5470.4 1671.24  5478.1 1672.80  5559.0 1673.30
#Mann=3,-1,0
  4078.2    0.05       0  4965.3    0.03       0  4971.3    0.05       0
Bank Sta=4965.3,4971.3
Exp/Cntr=0.3,0.1

Type RM Length L Ch R = 1,29827,612,612,612
BEGIN DESCRIPTION:
Mapping XS 88c66363
END DESCRIPTION:
XS GIS Cut Line= 2
      1586531.28      6915567.94      1586621.56      6914498.45
#Sta/Elev= 30
  4206.9 1671.24  4327.3 1672.04  4407.6 1670.28  4467.8 1671.08  4568.1 1669.45
  4658.4 1671.91  4688.5 1670.89  4738.7 1671.26  4778.9 1670.37  4785.0 1669.58
  4869.2 1669.94  4899.3 1669.12  4904.7 1668.29  4909.7 1669.46  4919.4 1668.75
  4936.3 1664.04  4936.8 1663.54  4942.0 1663.54  4942.5 1664.04  4959.5 1667.88
  4969.5 1668.42  4989.6 1667.29  4999.7 1664.69  5039.8 1664.14  5069.9 1664.49
  5079.9 1667.20  5090.0 1667.93  5170.3 1671.12  5220.4 1673.87  5280.2 1674.92
#Mann=3,-1,0
  4206.9    0.05       0  4936.3    0.03       0  4942.5    0.05       0
Bank Sta=4936.3,4942.5
Exp/Cntr=0.3,0.1

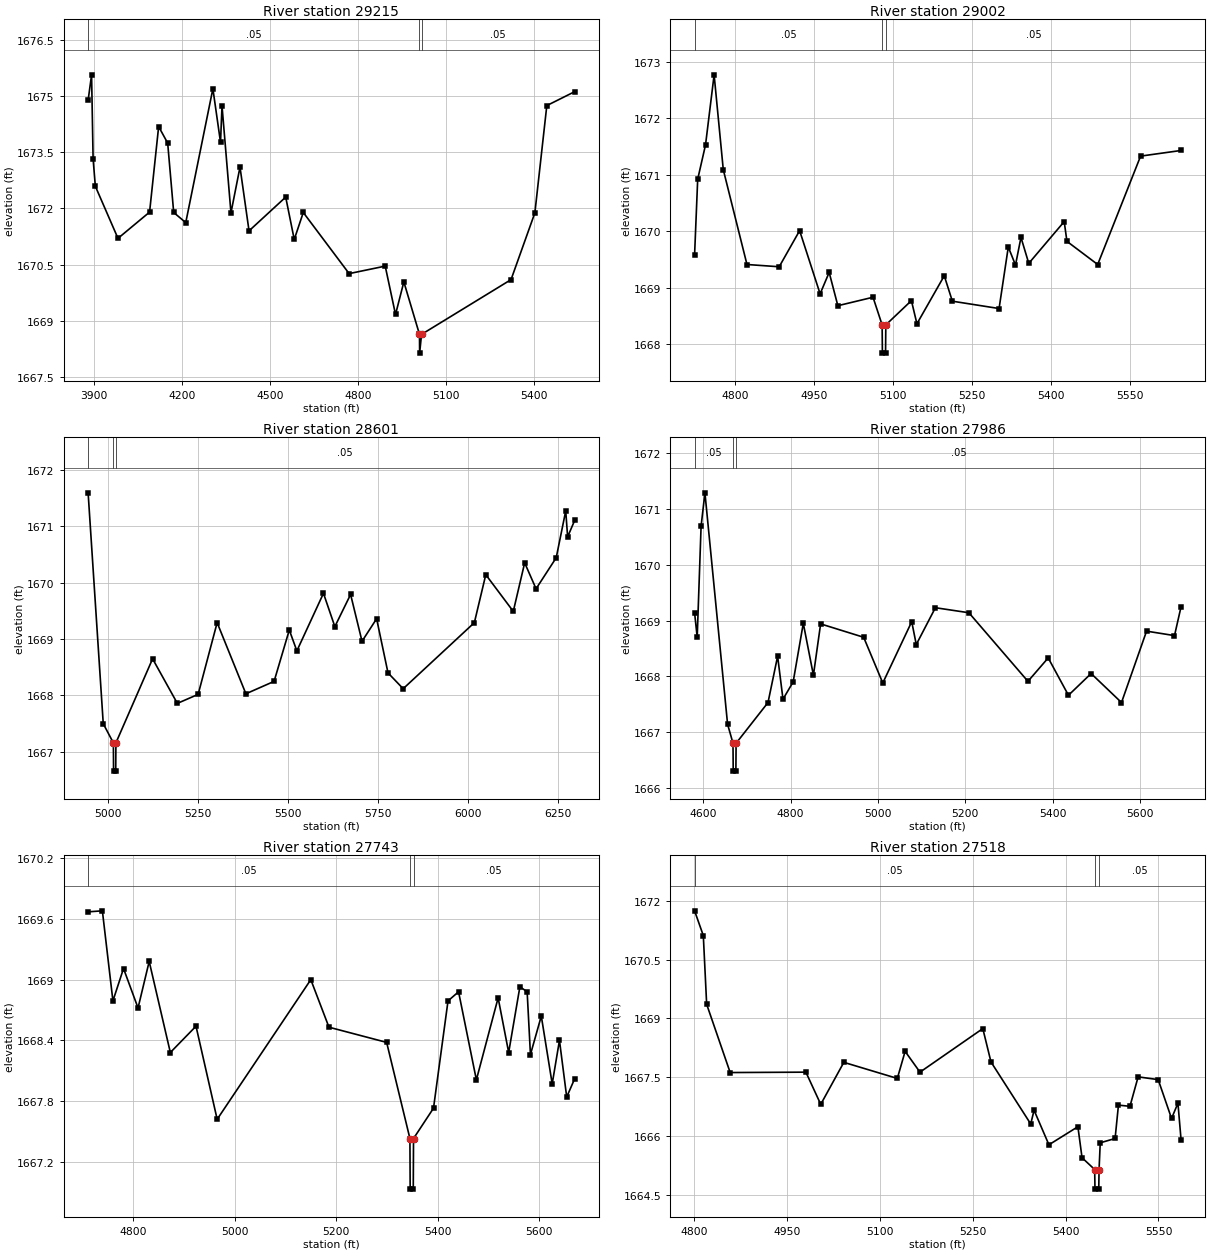
Type RM Length L Ch R = 1,29215,213,213,213
BEGIN DESCRIPTION:
Mapping XS 0a4aeabd
END DESCRIPTION:
XS GIS Cut Line= 4
      1587026.70      6915651.98      1587230.45      6914784.92
      1586984.87      6914510.67      1586591.69      6914439.99
#Sta/Elev= 30
  3880.8 1674.88  3892.6 1675.56  3897.8 1673.32  3905.4 1672.59  3982.6 1671.20
  4090.3 1671.90  4121.2 1674.18  4152.0 1673.74  4172.5 1671.89  4213.6 1671.62
  4306.1 1675.19  4332.1 1673.76  4337.2 1674.73  4367.7 1671.88  4398.5 1673.10
  4429.3 1671.40  4554.3 1672.30  4583.4 1671.17  4614.2 1671.89  4770.5 1670.26
  4893.5 1670.46  4928.6 1669.17  4957.0 1670.04  5010.3 1668.64  5010.8 1668.14
  5017.3 1668.64  5322.4 1670.10  5403.6 1671.88  5444.3 1674.74  5539.1 1675.11
#Mann=3,-1,0
  3880.8    0.05       0  5010.3    0.03       0  5017.3    0.05       0
Bank Sta=5010.3,5017.3
Exp/Cntr=0.3,0.1

Type RM Length L Ch R = 1,29002,401,401,401
BEGIN DESCRIPTION:
Mapping XS 4e1fcef0
END DESCRIPTION:
XS GIS Cut Line= 2
      1587470.64      6914528.60      1586582.80      6914272.63
#Sta/Elev= 30
  4723.7 1669.58  4729.6 1670.92  4744.5 1671.53  4760.8 1672.77  4778.2 1671.09
  4823.2 1669.41  4884.4 1669.37  4923.2 1670.01  4962.1 1668.89  4979.3 1669.27
  4995.8 1668.68  5062.6 1668.83  5079.9 1668.34  5080.4 1667.84  5086.4 1667.84
  5086.9 1668.34  5135.5 1668.77  5146.0 1668.36  5197.9 1669.21  5213.3 1668.76
  5302.0 1668.63  5319.5 1669.72  5333.2 1669.40  5343.6 1669.89  5358.4 1669.43
  5425.7 1670.17  5430.9 1669.82  5489.3 1669.41  5570.8 1671.33  5647.7 1671.43
#Mann=3,-1,0
  4723.7    0.05       0  5079.9    0.03       0  5086.9    0.05       0
Bank Sta=5079.9,5086.9
Exp/Cntr=0.3,0.1

Type RM Length L Ch R = 1,28601,615,615,615
BEGIN DESCRIPTION:
Mapping XS 8ad09f01
END DESCRIPTION:
XS GIS Cut Line= 2
      1587504.84      6914190.94      1586223.48      6913766.27
#Sta/Elev= 30
  4946.0 1671.59  4988.0 1667.50  5016.1 1667.16  5016.6 1666.66  5022.6 1666.66
  5023.1 1667.16  5124.9 1668.65  5193.6 1667.86  5251.3 1668.02  5304.0 1669.29
  5383.8 1668.03  5462.0 1668.25  5504.2 1669.16  5525.2 1668.79  5599.0 1669.81
  5630.6 1669.22  5674.3 1669.79  5706.0 1668.96  5746.5 1669.36  5778.1 1668.40
  5820.2 1668.12  6017.7 1669.29  6049.4 1670.14  6125.7 1669.49  6157.3 1670.35
  6188.9 1669.89  6244.8 1670.44  6271.2 1671.27  6276.5 1670.81  6295.9 1671.10
#Mann=3,-1,0
  4946.0    0.05       0  5016.1    0.03       0  5023.1    0.05       0
Bank Sta=5016.1,5023.1
Exp/Cntr=0.3,0.1

Type RM Length L Ch R = 1,27986,243,243,243
BEGIN DESCRIPTION:
Mapping XS 71ff755e
END DESCRIPTION:
XS GIS Cut Line= 2
      1587588.60      6913944.02      1586571.25      6913489.17
#Sta/Elev= 30
  4579.9 1669.14  4585.9 1668.70  4594.8 1670.69  4603.6 1671.29  4655.5 1667.14
  4667.9 1666.80  4668.4 1666.30  4674.5 1666.30  4675.0 1666.80  4748.1 1667.53
  4770.1 1668.36  4782.4 1667.59  4805.7 1667.90  4828.9 1668.95  4852.1 1668.02
  4868.6 1668.94  4967.2 1668.70  5011.0 1667.88  5077.3 1668.98  5087.7 1668.57
  5131.5 1669.23  5208.2 1669.14  5343.5 1667.91  5389.9 1668.33  5436.3 1667.66
  5488.2 1668.05  5557.8 1667.53  5615.2 1668.81  5679.2 1668.73  5694.3 1669.25
#Mann=3,-1,0
  4579.9    0.05       0  4667.9    0.03       0  4675.0    0.05       0
Bank Sta=4667.9,4675
Exp/Cntr=0.3,0.1

Type RM Length L Ch R = 1,27743,225,225,225
BEGIN DESCRIPTION:
Mapping XS a93be829
END DESCRIPTION:
XS GIS Cut Line= 2
      1587597.90      6913824.13      1586864.79      6913205.74
#Sta/Elev= 30
  4710.7 1669.67  4738.8 1669.68  4759.6 1668.79  4780.5 1669.11  4809.1 1668.72
  4831.1 1669.18  4872.8 1668.28  4923.4 1668.54  4965.1 1667.62  5149.7 1669.00
  5185.5 1668.53  5299.2 1668.38  5345.1 1667.43  5345.6 1666.93  5351.7 1666.93
  5352.2 1667.43  5391.6 1667.73  5420.2 1668.79  5441.0 1668.88  5476.1 1668.01
  5519.0 1668.82  5539.8 1668.28  5561.9 1668.93  5576.2 1668.88  5582.7 1668.26
  5604.1 1668.64  5625.6 1667.97  5639.9 1668.40  5654.2 1667.84  5669.8 1668.02
#Mann=3,-1,0
  4710.7    0.05       0  5345.1    0.05       0  5352.2    0.05       0
Bank Sta=5345.1,5352.2
Exp/Cntr=0.3,0.1

Type RM Length L Ch R = 1,27518,1259,1259,1259
BEGIN DESCRIPTION:
Mapping XS f6342d0b
END DESCRIPTION:
XS GIS Cut Line= 2
      1587637.33      6913711.18      1587339.90      6912983.74
#Sta/Elev= 30
  4800.6 1671.74  4814.7 1671.11  4820.1 1669.36  4858.1 1667.62  4980.4 1667.63
  5004.4 1666.81  5041.7 1667.88  5128.1 1667.47  5140.7 1668.16  5164.7 1667.63
  5266.2 1668.74  5279.4 1667.89  5343.6 1666.31  5349.0 1666.66  5373.0 1665.78
  5419.8 1666.24  5426.5 1665.45  5446.9 1665.15  5447.4 1664.65  5453.5 1664.65
  5454.0 1665.15  5455.9 1665.83  5479.9 1665.94  5485.3 1666.79  5503.9 1666.76
  5517.1 1667.51  5549.5 1667.44  5571.1 1666.45  5581.4 1666.84  5586.5 1665.90
#Mann=3,-1,0
  4800.6    0.05       0  5446.9    0.05       0  5454.0    0.05       0
Bank Sta=5446.9,5454
Exp/Cntr=0.3,0.1

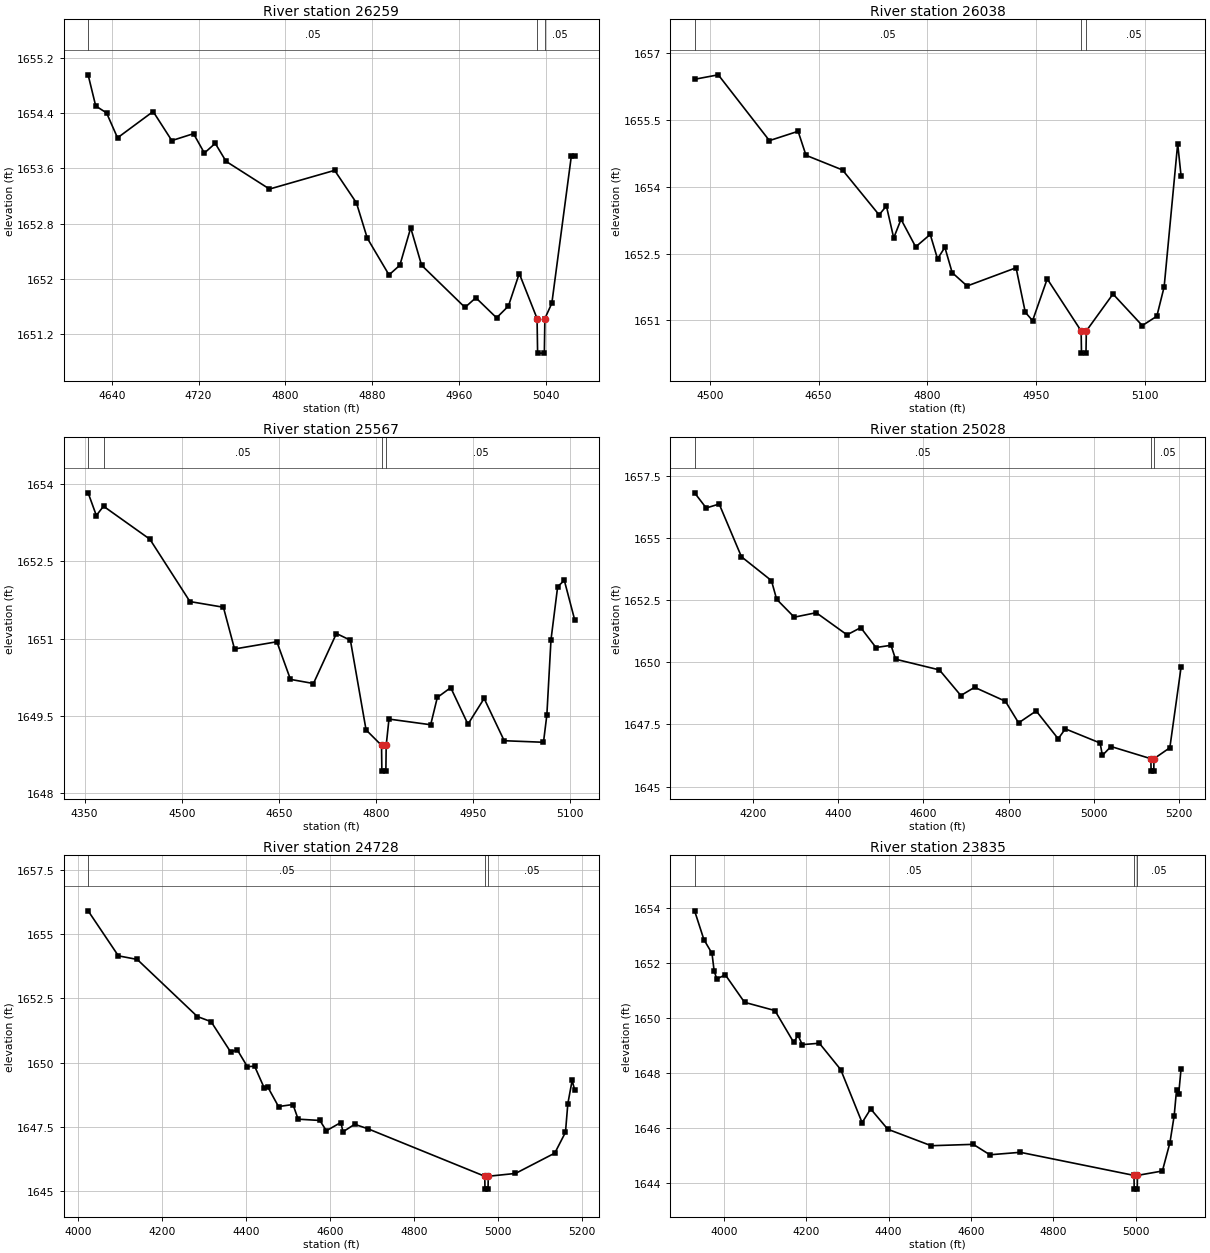
Type RM Length L Ch R = 1,26259,221,221,221
BEGIN DESCRIPTION:
Mapping XS bf9844a7
END DESCRIPTION:
XS GIS Cut Line= 2
      1588501.79      6913385.04      1588487.90      6912937.05
#Sta/Elev= 30
  4618.2 1654.95  4625.2 1654.50  4635.2 1654.40  4645.3 1654.04  4678.1 1654.42
  4695.3 1654.00  4715.3 1654.10  4725.3 1653.82  4735.3 1653.96  4745.3 1653.70
  4785.3 1653.30  4845.3 1653.57  4865.4 1653.10  4875.4 1652.59  4895.4 1652.06
  4905.4 1652.20  4915.4 1652.74  4925.4 1652.20  4965.4 1651.59  4975.4 1651.73
  4994.5 1651.44  5005.4 1651.61  5015.4 1652.08  5031.8 1651.43  5032.3 1650.93
  5038.5 1650.93  5039.0 1651.43  5045.4 1651.65  5063.4 1653.78  5066.4 1653.78
#Mann=3,-1,0
  4618.2    0.05       0  5031.8    0.03       0  5039.0    0.05       0
Bank Sta=5031.8,5039
Exp/Cntr=0.3,0.1

Type RM Length L Ch R = 1,26038,471,471,471
BEGIN DESCRIPTION:
Mapping XS b91ab8e5
END DESCRIPTION:
XS GIS Cut Line= 2
      1588600.31      6913620.41      1588690.14      6912954.84
#Sta/Elev= 30
  4478.9 1656.42  4511.6 1656.52  4582.2 1655.04  4621.8 1655.25  4632.7 1654.71
  4683.1 1654.38  4733.6 1653.37  4743.7 1653.57  4753.8 1652.85  4763.9 1653.27
  4784.1 1652.65  4804.2 1652.93  4814.3 1652.38  4824.4 1652.64  4834.5 1652.07
  4855.1 1651.77  4922.7 1652.18  4935.4 1651.18  4945.5 1650.99  4965.7 1651.93
  5012.5 1650.76  5013.0 1650.26  5019.2 1650.26  5019.7 1650.76  5056.5 1651.59
  5096.9 1650.88  5117.0 1651.09  5127.1 1651.75  5145.8 1654.97  5150.5 1654.24
#Mann=3,-1,0
  4478.9    0.05       0  5012.5    0.05       0  5019.7    0.05       0
Bank Sta=5012.5,5019.7
Exp/Cntr=0.3,0.1

Type RM Length L Ch R = 1,25567,539,539,539
BEGIN DESCRIPTION:
Mapping XS 826cebd5
END DESCRIPTION:
XS GIS Cut Line= 2
      1588902.99      6913710.34      1589091.04      6912982.64
#Sta/Elev= 30
  4355.3 1653.83  4368.0 1653.39  4379.1 1653.57  4450.7 1652.93  4512.6 1651.72
  4564.3 1651.61  4581.5 1650.80  4646.9 1650.94  4667.9 1650.21  4703.4 1650.13
  4738.9 1651.10  4760.5 1650.97  4784.7 1649.23  4808.6 1648.93  4809.1 1648.43
  4815.3 1648.43  4815.8 1648.93  4820.1 1649.44  4884.5 1649.33  4894.8 1649.86
  4915.5 1650.05  4942.1 1649.34  4967.1 1649.84  4998.1 1649.02  5058.8 1648.99
  5064.0 1649.52  5070.4 1650.98  5080.7 1652.01  5091.0 1652.13  5106.9 1651.37
#Mann=4,-1,0
  4355.3    0.12       0  4379.1    0.05       0  4808.6    0.05       0
  4815.8    0.05       0
Bank Sta=4808.6,4815.8
Exp/Cntr=0.3,0.1

Type RM Length L Ch R = 1,25028,300,300,300
BEGIN DESCRIPTION:
Mapping XS 6fb634fd
END DESCRIPTION:
XS GIS Cut Line= 2
      1589314.58      6914144.49      1589596.86      6913038.65
#Sta/Elev= 30
  4063.2 1656.81  4090.5 1656.20  4120.9 1656.36  4173.1 1654.24  4243.5 1653.28
  4255.7 1652.53  4297.0 1651.81  4348.6 1651.99  4420.8 1651.10  4453.0 1651.39
  4488.7 1650.59  4524.0 1650.68  4534.7 1650.12  4637.5 1649.69  4687.8 1648.66
  4720.1 1648.99  4792.3 1648.43  4823.3 1647.56  4864.6 1648.04  4916.2 1646.92
  4932.9 1647.32  5014.6 1646.75  5019.8 1646.25  5040.0 1646.61  5133.6 1646.12
  5134.1 1645.62  5140.4 1645.62  5140.9 1646.12  5178.1 1646.56  5204.5 1649.80
#Mann=3,-1,0
  4063.2    0.05       0  5133.6    0.05       0  5140.9    0.05       0
Bank Sta=5133.6,5140.9
Exp/Cntr=0.3,0.1

Type RM Length L Ch R = 1,24728,893,893,893
BEGIN DESCRIPTION:
Mapping XS be4f5e42
END DESCRIPTION:
XS GIS Cut Line= 2
      1589510.52      6914240.72      1589815.83      6913122.35
#Sta/Elev= 30
  4024.1 1655.90  4096.2 1654.15  4141.1 1654.01  4284.4 1651.79  4317.2 1651.59
  4363.8 1650.41  4379.4 1650.50  4403.6 1649.84  4420.8 1649.86  4443.3 1649.03
  4451.9 1649.06  4477.8 1648.29  4512.3 1648.37  4524.5 1647.80  4576.3 1647.75
  4591.8 1647.35  4626.3 1647.67  4631.5 1647.31  4659.2 1647.60  4690.3 1647.43
  4969.3 1645.58  4969.8 1645.08  4977.1 1645.08  4977.6 1645.58  5042.5 1645.69
  5136.1 1646.48  5161.6 1647.29  5167.2 1648.40  5177.5 1649.31  5183.4 1648.94
#Mann=3,-1,0
  4024.1    0.05       0  4969.3    0.03       0  4977.6    0.05       0
Bank Sta=4969.3,4977.6
Exp/Cntr=0.3,0.1

Type RM Length L Ch R = 1,23835,189,189,189
BEGIN DESCRIPTION:
Mapping XS fc335fea
END DESCRIPTION:
XS GIS Cut Line= 2
      1590257.65      6914469.87      1590572.83      6913331.91
#Sta/Elev= 30
  3929.2 1653.91  3951.9 1652.86  3971.5 1652.36  3976.6 1651.73  3983.0 1651.43
  4003.8 1651.58  4050.4 1650.58  4124.2 1650.28  4169.8 1649.12  4180.2 1649.38
  4190.5 1649.04  4232.1 1649.09  4283.9 1648.13  4335.8 1646.20  4356.6 1646.70
  4398.1 1645.96  4503.5 1645.36  4605.6 1645.41  4645.9 1645.03  4719.7 1645.12
  4995.7 1644.28  4996.2 1643.78  5003.6 1643.78  5004.1 1644.28  5064.6 1644.44
  5082.9 1645.47  5093.3 1646.46  5098.9 1647.38  5104.1 1647.23  5110.0 1648.17
#Mann=3,-1,0
  3929.2    0.05       0  4995.7    0.05       0  5004.1    0.05       0
Bank Sta=4995.7,5004.1
Exp/Cntr=0.3,0.1

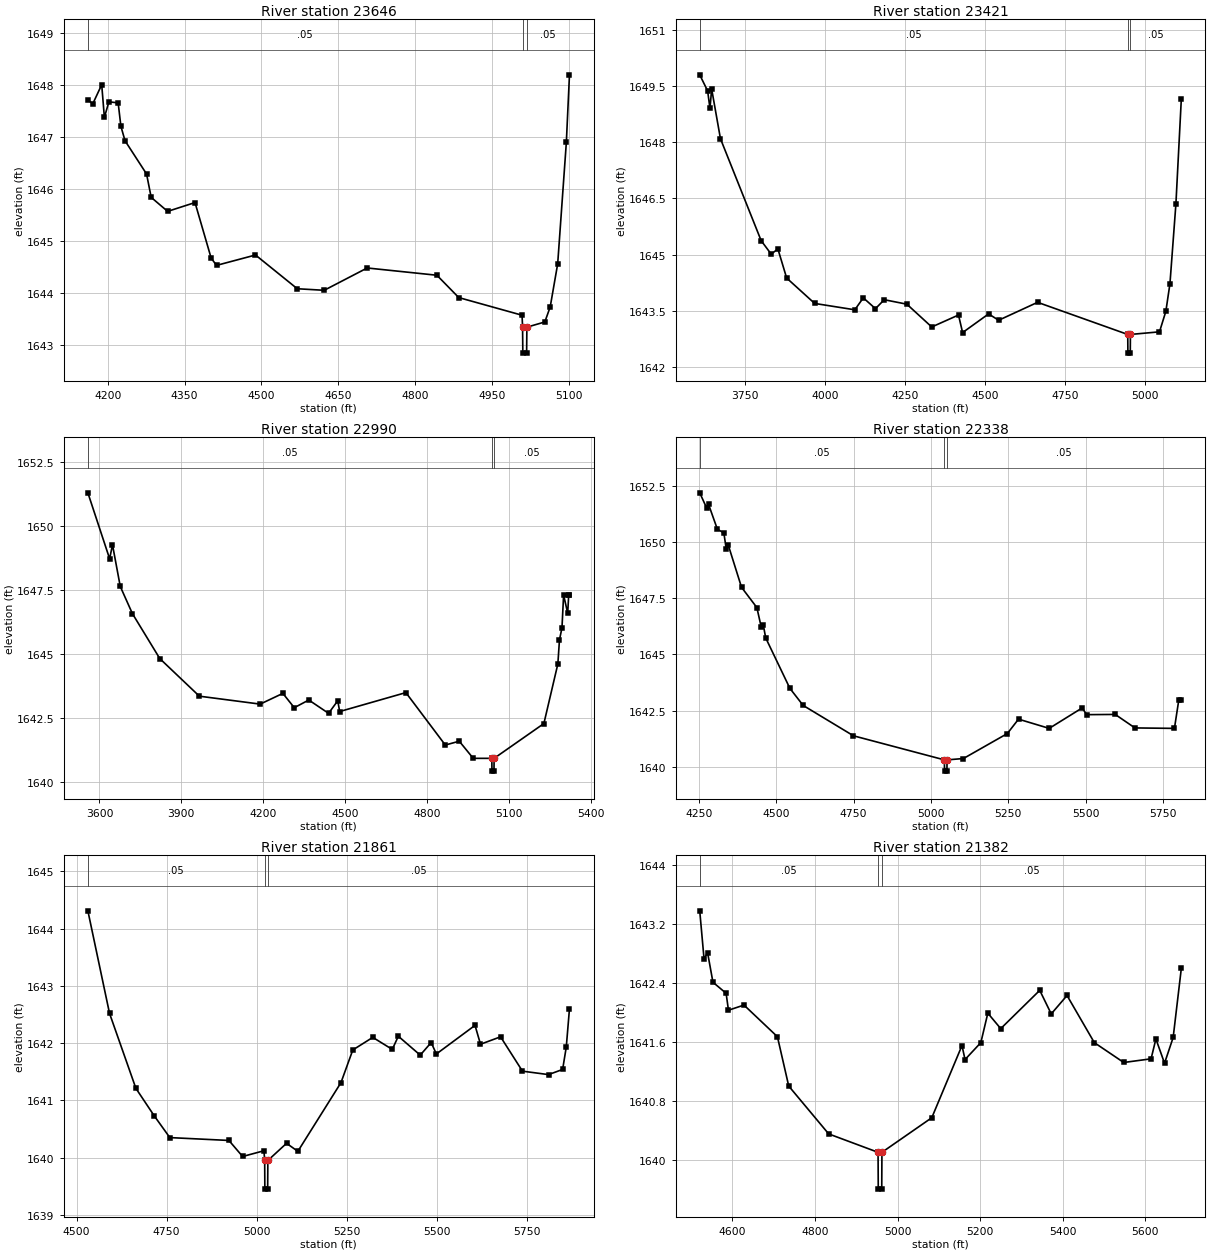
Type RM Length L Ch R = 1,23646,225,225,225
BEGIN DESCRIPTION:
Mapping XS 4b991da7
END DESCRIPTION:
XS GIS Cut Line= 2
      1590461.28      6914287.08      1590747.32      6913392.18
#Sta/Elev= 30
  4161.4 1647.72  4170.9 1647.64  4188.4 1648.01  4193.6 1647.38  4202.4 1647.68
  4220.5 1647.66  4225.8 1647.21  4233.9 1646.93  4275.9 1646.29  4284.9 1645.84
  4317.0 1645.57  4370.4 1645.74  4401.9 1644.67  4412.4 1644.53  4488.4 1644.73
  4569.9 1644.08  4622.4 1644.05  4706.3 1644.48  4842.3 1644.34  4884.9 1643.91
  5008.4 1643.57  5009.4 1643.34  5009.9 1642.84  5017.3 1642.84  5017.8 1643.34
  5052.8 1643.44  5063.3 1643.73  5077.9 1644.56  5094.8 1646.90  5100.9 1648.20
#Mann=3,-1,0
  4161.4    0.05       0  5009.4    0.05       0  5017.8    0.05       0
Bank Sta=5009.4,5017.8
Exp/Cntr=0.3,0.1

Type RM Length L Ch R = 1,23421,431,431,431
BEGIN DESCRIPTION:
Mapping XS 7e4d2d10
END DESCRIPTION:
XS GIS Cut Line= 2
      1590510.01      6914881.66      1590951.27      6913441.76
#Sta/Elev= 30
  3608.3 1649.81  3633.0 1649.38  3640.3 1648.91  3645.6 1649.43  3673.1 1648.10
  3800.4 1645.37  3831.8 1645.01  3852.7 1645.15  3880.1 1644.37  3967.7 1643.69
  4093.2 1643.52  4119.8 1643.84  4157.8 1643.55  4185.3 1643.79  4256.0 1643.67
  4333.8 1643.06  4417.5 1643.38  4430.3 1642.91  4511.6 1643.41  4543.0 1643.24
  4664.8 1643.72  4946.7 1642.86  4947.2 1642.36  4954.6 1642.36  4955.1 1642.86
  5046.0 1642.93  5065.9 1643.48  5078.7 1644.22  5097.3 1646.35  5114.3 1649.17
#Mann=3,-1,0
  3608.3    0.05       0  4946.7    0.03       0  4955.1    0.05       0
Bank Sta=4946.7,4955.1
Exp/Cntr=0.3,0.1

Type RM Length L Ch R = 1,22990,652,652,652
BEGIN DESCRIPTION:
Mapping XS fd6dc3fc
END DESCRIPTION:
XS GIS Cut Line= 3
      1590586.40      6914954.67      1590852.04      6914034.88
      1591526.14      6913589.91
#Sta/Elev= 30
  3557.5 1651.31  3637.3 1648.73  3647.7 1649.28  3676.2 1647.65  3720.6 1646.59
  3821.1 1644.83  3966.1 1643.36  4189.0 1643.05  4272.2 1643.47  4313.9 1642.91
  4367.2 1643.21  4439.7 1642.69  4473.3 1643.18  4480.4 1642.76  4723.0 1643.50
  4867.5 1641.45  4918.7 1641.60  4969.9 1640.93  5038.0 1640.93  5038.5 1640.43
  5045.9 1640.43  5046.4 1640.93  5228.8 1642.29  5280.0 1644.62  5286.0 1645.57
  5295.1 1646.03  5301.1 1647.32  5316.1 1646.60  5319.8 1647.33  5322.6 1647.33
#Mann=3,-1,0
  3557.5    0.05       0  5038.0    0.05       0  5046.4    0.05       0
Bank Sta=5038,5046.4
Exp/Cntr=0.3,0.1

Type RM Length L Ch R = 1,22338,477,477,477
BEGIN DESCRIPTION:
Mapping XS fa6517b5
END DESCRIPTION:
XS GIS Cut Line= 2
      1590931.75      6914914.82      1591934.54      6913726.09
#Sta/Elev= 30
  4253.4 1652.18  4275.3 1651.52  4281.8 1651.67  4310.4 1650.56  4331.3 1650.40
  4339.0 1649.68  4345.5 1649.86  4388.4 1647.98  4437.9 1647.08  4452.2 1646.20
  4458.7 1646.30  4466.5 1645.73  4544.5 1643.49  4587.4 1642.73  4749.9 1641.38
  5043.4 1640.31  5043.9 1639.81  5051.6 1639.81  5052.1 1640.31  5104.9 1640.37
  5246.7 1641.48  5282.8 1642.12  5381.9 1641.71  5488.5 1642.62  5502.8 1642.32
  5595.1 1642.33  5658.8 1641.73  5786.3 1641.71  5800.6 1642.99  5808.6 1642.97
#Mann=3,-1,0
  4253.4    0.05       0  5043.4    0.04       0  5052.1    0.05       0
Bank Sta=5043.4,5052.1
Exp/Cntr=0.3,0.1

Type RM Length L Ch R = 1,21861,479,479,479
BEGIN DESCRIPTION:
Mapping XS 99f573b8
END DESCRIPTION:
XS GIS Cut Line= 3
      1591635.14      6915035.51      1591855.99      6914311.61
      1591950.03      6913739.23
#Sta/Elev= 30
  4531.4 1644.31  4591.5 1642.52  4664.7 1641.21  4715.6 1640.73  4758.9 1640.35
  4922.9 1640.30  4961.0 1640.02  5020.2 1640.12  5022.2 1639.95  5022.7 1639.45
  5030.5 1639.45  5031.0 1639.95  5082.9 1640.25  5114.3 1640.11  5234.0 1641.31
  5266.8 1641.88  5322.3 1642.10  5376.4 1641.89  5393.2 1642.12  5454.0 1641.79
  5484.4 1642.01  5498.8 1641.81  5606.1 1642.31  5621.3 1641.98  5677.0 1642.11
  5737.8 1641.51  5810.1 1641.45  5849.3 1641.54  5859.4 1641.93  5868.3 1642.60
#Mann=3,-1,0
  4531.4    0.05       0  5022.2    0.04       0  5031.0    0.05       0
Bank Sta=5022.2,5031
Exp/Cntr=0.3,0.1

Type RM Length L Ch R = 1,21382,422,422,422
BEGIN DESCRIPTION:
Mapping XS 2c9f0e0c
END DESCRIPTION:
XS GIS Cut Line= 3
      1592383.61      6914814.68      1592146.38      6914393.41
      1591950.06      6913738.99
#Sta/Elev= 30
  4520.8 1643.38  4531.2 1642.73  4539.9 1642.81  4552.8 1642.41  4584.7 1642.26
  4590.4 1642.03  4628.0 1642.10  4709.0 1641.67  4736.4 1641.00  4833.2 1640.35
  4952.8 1640.10  4953.3 1639.60  4961.7 1639.60  4962.2 1640.10  5083.0 1640.57
  5156.1 1641.55  5163.5 1641.36  5201.8 1641.59  5218.7 1641.99  5250.0 1641.78
  5344.5 1642.30  5372.3 1641.98  5410.6 1642.23  5476.7 1641.59  5548.0 1641.32
  5614.2 1641.37  5625.9 1641.64  5646.8 1641.31  5667.7 1641.66  5687.5 1642.60
#Mann=3,-1,0
  4520.8    0.05       0  4952.8    0.05       0  4962.2    0.05       0
Bank Sta=4952.8,4962.2
Exp/Cntr=0.3,0.1

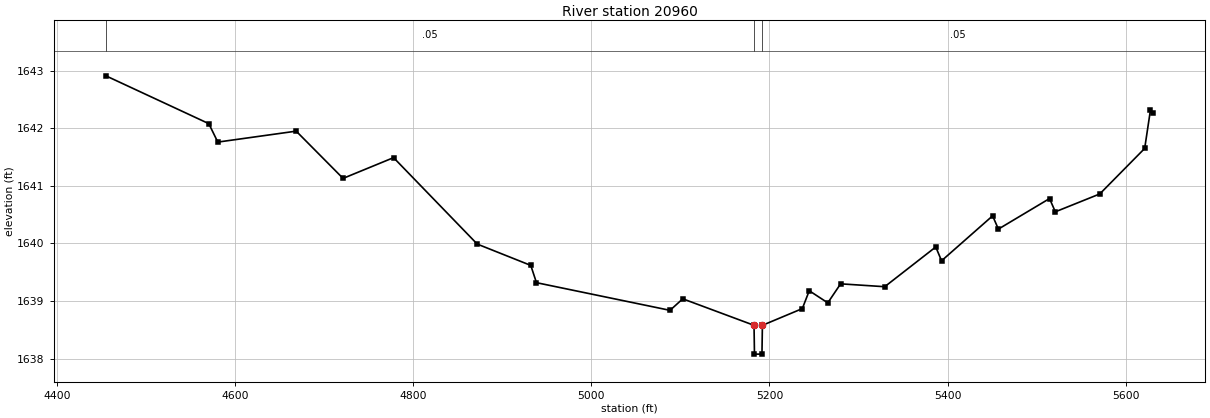
Type RM Length L Ch R = 1,20960,445,445,445
BEGIN DESCRIPTION:
Mapping XS ede71f6e
END DESCRIPTION:
XS GIS Cut Line= 3
      1592480.00      6914663.04      1592522.31      6914207.55
      1591968.87      6913750.22
#Sta/Elev= 30
  4455.2 1642.91  4570.7 1642.08  4580.8 1641.76  4668.8 1641.95  4721.4 1641.13
  4778.1 1641.49  4872.0 1639.99  4932.1 1639.62  4938.5 1639.32  5088.4 1638.84
  5102.7 1639.04  5182.7 1638.58  5183.2 1638.08  5191.6 1638.08  5192.1 1638.58
  5236.9 1638.87  5244.7 1639.18  5265.5 1638.97  5279.9 1639.30  5329.4 1639.25
  5386.7 1639.94  5393.2 1639.70  5450.5 1640.48  5457.0 1640.25  5514.4 1640.78
  5520.9 1640.55  5570.8 1640.86  5621.2 1641.65  5627.7 1642.32  5630.6 1642.26
#Mann=3,-1,0
  4455.2    0.05       0  5182.7    0.05       0  5192.1    0.05       0
Bank Sta=5182.7,5192.1
Exp/Cntr=0.3,0.1