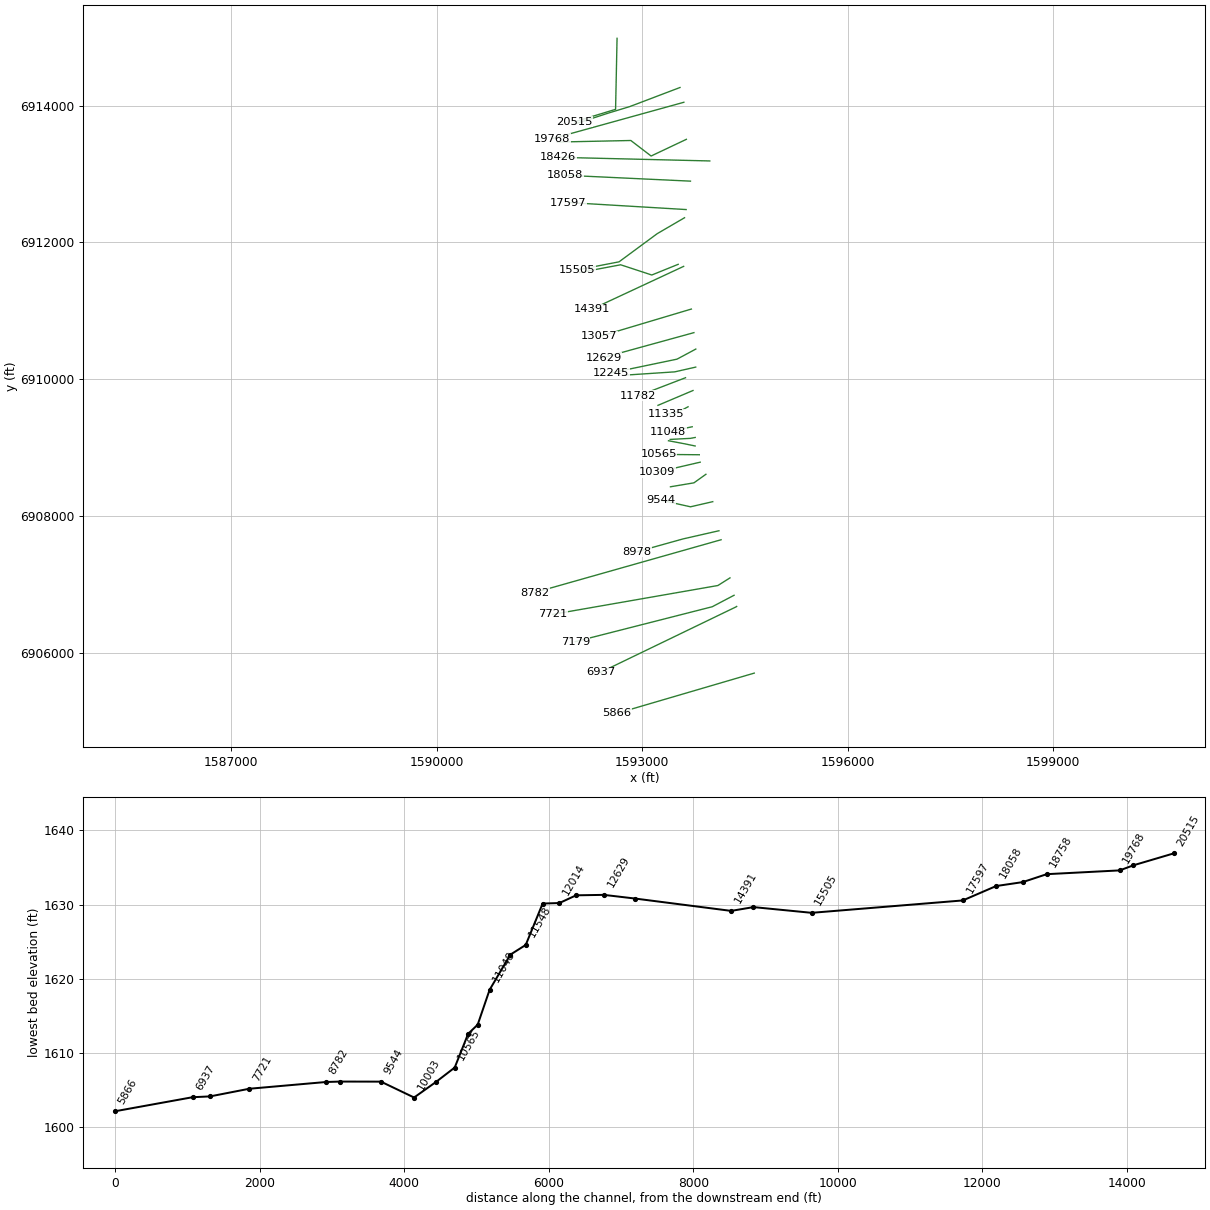
HEC-RAS study Deadman 12.prj: Deadman 12 Base Level Engineering

--- Deadman 12.g01 (geometry) --- (continued)

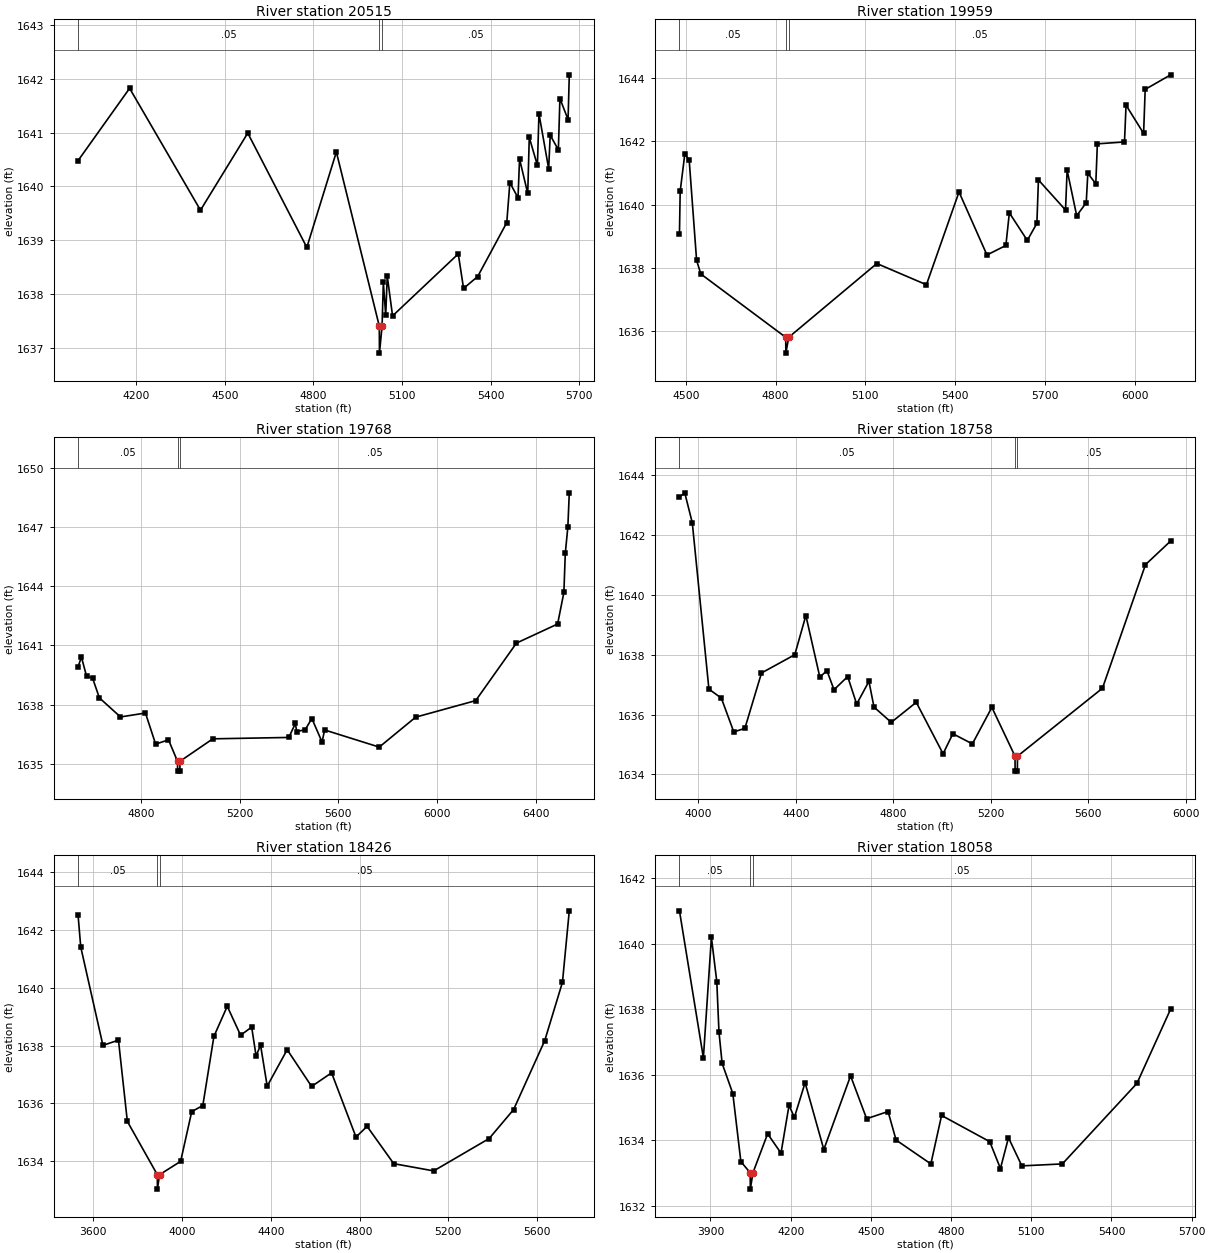
Type RM Length L Ch R = 1,20515,556,556,556
BEGIN DESCRIPTION:
Mapping XS c3006bc8
END DESCRIPTION:
XS GIS Cut Line= 3
      1592632.80      6914982.36      1592611.10      6913945.05
      1592012.54      6913762.88
#Sta/Elev= 30
  4003.1 1640.48  4177.5 1641.82  4417.5 1639.56  4577.6 1640.99  4777.6 1638.87
  4877.6 1640.64  5023.0 1637.41  5023.5 1636.91  5032.4 1637.41  5036.7 1638.22
  5044.7 1637.61  5049.9 1638.34  5067.9 1637.60  5290.4 1638.75  5308.3 1638.11
  5356.1 1638.33  5454.6 1639.33  5465.1 1640.07  5492.7 1639.79  5497.9 1640.51
  5525.6 1639.87  5530.8 1640.91  5558.4 1640.39  5563.6 1641.35  5596.5 1640.33
  5601.7 1640.95  5629.3 1640.68  5634.6 1641.63  5662.2 1641.24  5666.3 1642.07
#Mann=3,-1,0
  4003.1    0.05       0  5023.0    0.05       0  5032.4    0.05       0
Bank Sta=5023,5032.4
Exp/Cntr=0.3,0.1

Type RM Length L Ch R = 1,19959,191,191,191
BEGIN DESCRIPTION:
Mapping XS b08d8536
END DESCRIPTION:
XS GIS Cut Line= 4
      1593551.75      6914264.02      1592817.85      6913985.07
      1592512.35      6913892.09      1592000.99      6913726.06
#Sta/Elev= 30
  4478.6 1639.08  4481.0 1640.42  4496.5 1641.60  4511.1 1641.41  4535.9 1638.24
  4550.0 1637.81  4833.8 1635.81  4834.3 1635.31  4843.9 1635.81  5138.4 1638.14
  5304.2 1637.47  5413.2 1640.40  5506.6 1638.41  5569.8 1638.71  5581.5 1639.74
  5641.5 1638.87  5673.5 1639.41  5678.7 1640.78  5769.3 1639.83  5774.6 1641.09
  5806.6 1639.65  5838.5 1640.06  5843.8 1640.99  5870.5 1640.66  5875.7 1641.92
  5966.4 1641.98  5971.6 1643.14  6030.3 1642.25  6035.6 1643.64  6120.7 1644.10
#Mann=3,-1,0
  4478.6    0.05       0  4833.8    0.03       0  4843.9    0.05       0
Bank Sta=4833.8,4843.9
Exp/Cntr=0.3,0.1

Type RM Length L Ch R = 1,19768,1010,1010,1010
BEGIN DESCRIPTION:
Mapping XS c4aec314
END DESCRIPTION:
XS GIS Cut Line= 2
      1593608.12      6914048.15      1591689.38      6913517.01
#Sta/Elev= 30
  4544.9 1639.93  4558.5 1640.41  4579.3 1639.43  4603.4 1639.35  4631.1 1638.34
  4716.7 1637.37  4817.9 1637.57  4859.2 1635.99  4911.3 1636.21  4947.8 1635.12
  4948.3 1634.62  4957.4 1634.62  4957.9 1635.12  5090.9 1636.26  5399.0 1636.33
  5425.6 1637.04  5430.8 1636.63  5465.1 1636.72  5492.4 1637.29  5533.7 1636.10
  5544.2 1636.71  5765.5 1635.84  5913.1 1637.36  6156.4 1638.20  6321.6 1641.12
  6488.5 1642.09  6513.9 1643.69  6519.6 1645.68  6530.0 1647.01  6535.8 1648.75
#Mann=3,-1,0
  4544.9    0.05       0  4947.8    0.03       0  4957.9    0.05       0
Bank Sta=4947.8,4957.9
Exp/Cntr=0.3,0.1

Type RM Length L Ch R = 1,18758,332,332,332
BEGIN DESCRIPTION:
Mapping XS 9a0c2ce0
END DESCRIPTION:
XS GIS Cut Line= 4
      1593644.64      6913506.88      1593130.00      6913263.00
      1592833.78      6913489.74      1591761.85      6913467.05
#Sta/Elev= 30
  3923.0 1643.27  3944.7 1643.41  3975.6 1642.41  4043.8 1636.85  4094.8 1636.55
  4145.8 1635.42  4191.3 1635.54  4259.5 1637.39  4396.0 1638.00  4441.5 1639.31
  4498.8 1637.25  4527.8 1637.47  4556.9 1636.83  4613.0 1637.27  4649.9 1636.35
  4700.2 1637.11  4721.0 1636.25  4791.7 1635.74  4894.3 1636.41  5004.3 1634.69
  5044.4 1635.36  5124.4 1635.02  5204.4 1636.24  5299.3 1634.61  5299.8 1634.11
  5309.0 1634.11  5309.5 1634.61  5658.0 1636.88  5834.5 1641.01  5937.7 1641.80
#Mann=3,-1,0
  3923.0    0.05       0  5299.3    0.05       0  5309.5    0.05       0
Bank Sta=5299.3,5309.5
Exp/Cntr=0.3,0.1

Type RM Length L Ch R = 1,18426,368,368,368
BEGIN DESCRIPTION:
Mapping XS b47b488c
END DESCRIPTION:
XS GIS Cut Line= 2
      1593986.87      6913190.94      1591774.21      6913244.11
#Sta/Elev= 30
  3532.0 1642.50  3543.9 1641.41  3643.9 1638.01  3713.9 1638.19  3753.9 1635.38
  3888.9 1633.54  3889.4 1633.04  3899.1 1633.54  3994.0 1634.00  4044.0 1635.72
  4094.0 1635.93  4144.0 1638.32  4204.1 1639.36  4264.1 1638.36  4314.1 1638.64
  4334.1 1637.64  4354.1 1638.02  4384.1 1636.60  4474.1 1637.86  4584.2 1636.59
  4674.2 1637.06  4784.2 1634.84  4834.2 1635.21  4954.3 1633.92  5134.3 1633.67
  5384.4 1634.79  5494.4 1635.79  5634.5 1638.17  5714.5 1640.19  5745.3 1642.66
#Mann=3,-1,0
  3532.0    0.05       0  3888.9    0.05       0  3899.1    0.05       0
Bank Sta=3888.9,3899.1
Exp/Cntr=0.3,0.1

Type RM Length L Ch R = 1,18058,461,461,461
BEGIN DESCRIPTION:
Mapping XS 0d3734c4
END DESCRIPTION:
XS GIS Cut Line= 2
      1593704.41      6912895.91      1591869.03      6912982.20
#Sta/Elev= 30
  3784.0 1641.01  3873.5 1636.52  3903.5 1640.20  3923.6 1638.85  3931.8 1637.31
  3943.6 1636.35  3983.6 1635.43  4013.7 1633.35  4048.6 1633.01  4049.1 1632.51
  4058.9 1633.01  4113.8 1634.20  4163.8 1633.61  4193.9 1635.07  4213.9 1634.70
  4253.9 1635.76  4324.0 1633.72  4424.1 1635.97  4484.2 1634.66  4564.3 1634.88
  4594.3 1634.01  4724.4 1633.28  4764.5 1634.76  4944.7 1633.96  4984.7 1633.14
  5014.8 1634.08  5064.8 1633.22  5216.3 1633.28  5495.3 1635.74  5621.4 1638.01
#Mann=3,-1,0
  3784.0    0.05       0  4048.6    0.05       0  4058.9    0.05       0
Bank Sta=4048.6,4058.9
Exp/Cntr=0.3,0.1

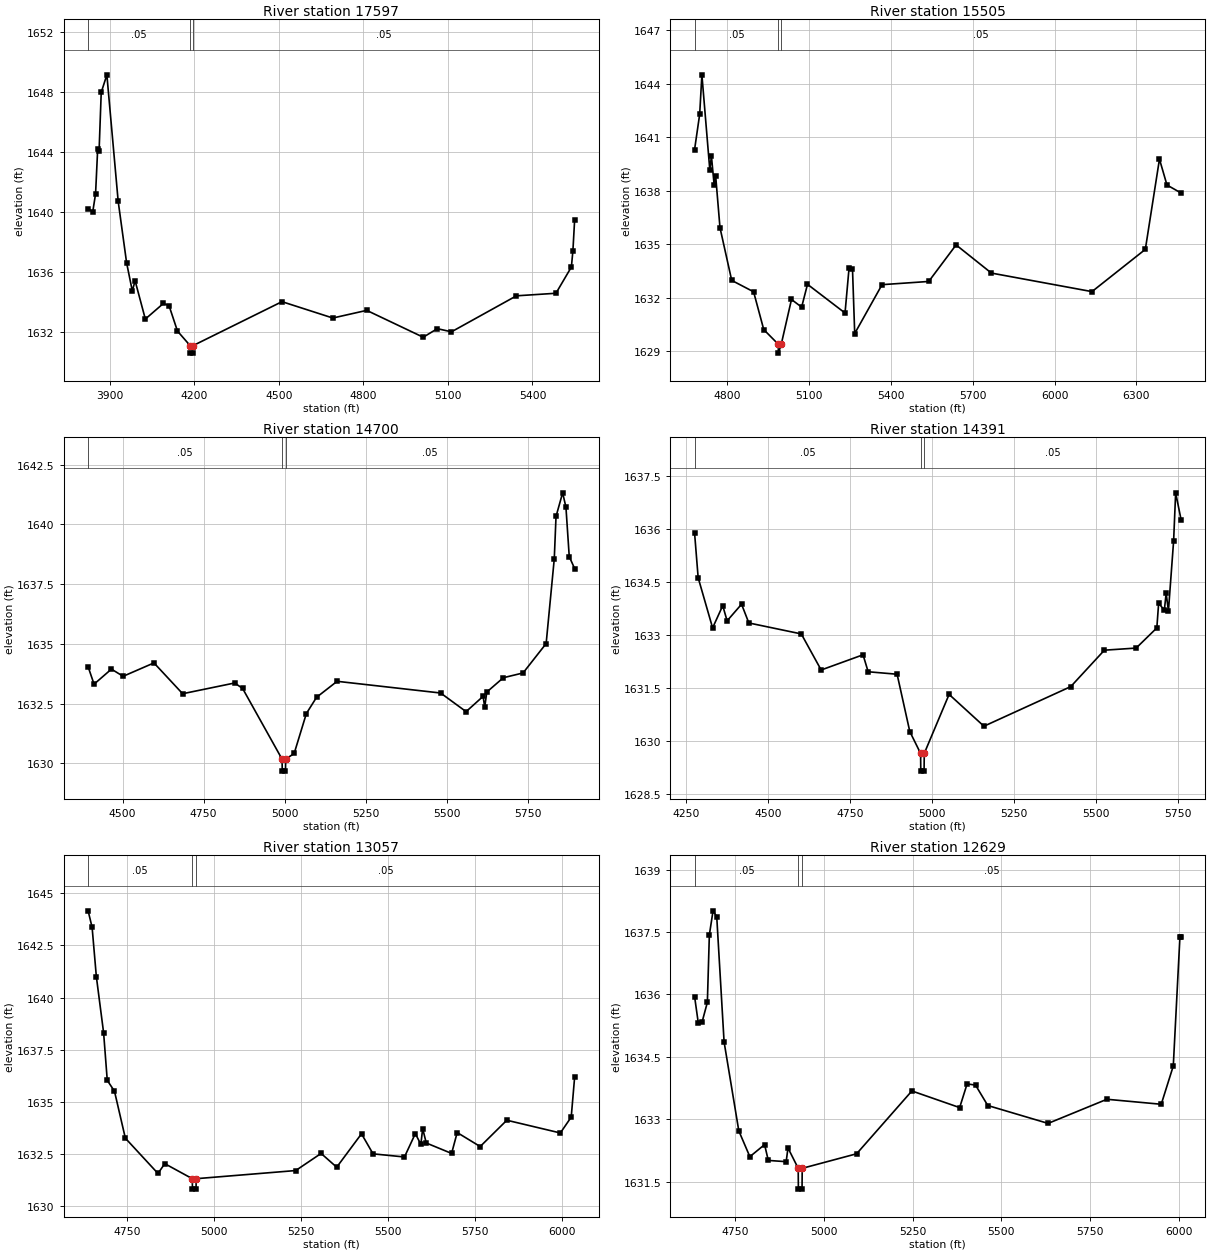
Type RM Length L Ch R = 1,17597,2092,2092,2092
BEGIN DESCRIPTION:
Mapping XS 0ab566c0
END DESCRIPTION:
XS GIS Cut Line= 2
      1593641.38      6912480.83      1591918.95      6912583.71
#Sta/Elev= 30
  3824.0 1640.19  3840.4 1639.99  3850.4 1641.18  3857.9 1644.17  3862.9 1644.05
  3870.5 1647.95  3890.5 1649.12  3930.6 1640.69  3960.6 1636.58  3980.7 1634.72
  3990.7 1635.39  4026.9 1632.84  4090.9 1633.88  4110.9 1633.74  4140.9 1632.04
  4185.8 1631.07  4186.3 1630.57  4195.6 1630.57  4196.1 1631.07  4511.6 1634.00
  4691.9 1632.91  4812.1 1633.42  5012.5 1631.63  5062.6 1632.20  5112.7 1631.99
  5343.1 1634.39  5483.3 1634.56  5538.0 1636.31  5543.4 1637.39  5549.5 1639.44
#Mann=3,-1,0
  3824.0    0.05       0  4185.8    0.05       0  4196.1    0.05       0
Bank Sta=4185.8,4196.1
Exp/Cntr=0.3,0.1

Type RM Length L Ch R = 1,15505,805,805,805
BEGIN DESCRIPTION:
Mapping XS 04eab62e
END DESCRIPTION:
XS GIS Cut Line= 4
      1593618.12      6912361.29      1593219.64      6912128.84
      1592661.78      6911717.09      1592044.13      6911597.54
#Sta/Elev= 30
  4680.2 1640.32  4698.9 1642.30  4707.0 1644.51  4736.1 1639.16  4741.9 1639.96
  4751.8 1638.35  4757.6 1638.82  4773.3 1635.94  4816.3 1632.98  4896.6 1632.34
  4933.8 1630.22  4987.0 1629.40  4987.5 1628.90  4998.0 1629.40  5035.5 1631.91
  5072.7 1631.48  5094.2 1632.76  5231.8 1631.15  5246.5 1633.66  5259.2 1633.62
  5267.3 1630.00  5367.5 1632.74  5538.7 1632.92  5639.0 1634.97  5768.5 1633.39
  6137.2 1632.35  6332.9 1634.72  6384.7 1639.78  6412.2 1638.33  6464.0 1637.88
#Mann=3,-1,0
  4680.2    0.05       0  4987.0   0.035       0  4998.0    0.05       0
Bank Sta=4987,4998
Exp/Cntr=0.3,0.1

Type RM Length L Ch R = 1,14700,309,309,309
BEGIN DESCRIPTION:
Mapping XS e0d72ef3
END DESCRIPTION:
XS GIS Cut Line= 4
      1593525.17      6911680.57      1593139.95      6911524.49
      1592685.02      6911673.92      1592088.65      6911561.27
#Sta/Elev= 30
  4393.5 1634.04  4411.8 1633.31  4465.4 1633.94  4501.6 1633.64  4596.7 1634.20
  4685.2 1632.91  4845.9 1633.36  4870.3 1633.13  4992.1 1630.17  4992.6 1629.67
  5002.6 1629.67  5003.1 1630.17  5029.4 1630.41  5067.0 1632.08  5098.5 1632.76
  5161.9 1633.43  5481.4 1632.94  5560.0 1632.16  5612.4 1632.80  5617.5 1632.35
  5623.8 1632.98  5674.9 1633.58  5735.8 1633.78  5807.0 1635.01  5832.1 1638.56
  5837.5 1640.33  5857.9 1641.32  5868.1 1640.72  5878.3 1638.65  5894.9 1638.15
#Mann=3,-1,0
  4393.5    0.05       0  4992.1   0.035       0  5003.1    0.05       0
Bank Sta=4992.1,5003.1
Exp/Cntr=0.3,0.1

Type RM Length L Ch R = 1,14391,1334,1334,1334
BEGIN DESCRIPTION:
Mapping XS 1a3f58de
END DESCRIPTION:
XS GIS Cut Line= 2
      1593604.86      6911650.68      1592259.99      6911023.08
#Sta/Elev= 30
  4275.7 1635.89  4286.6 1634.63  4330.7 1633.21  4361.6 1633.84  4374.9 1633.41
  4419.0 1633.88  4441.2 1633.35  4601.2 1633.04  4661.8 1632.02  4789.6 1632.45
  4805.2 1631.97  4893.5 1631.90  4932.2 1630.28  4965.2 1629.66  4965.7 1629.16
  4975.8 1629.16  4976.3 1629.66  5052.1 1631.33  5158.4 1630.43  5423.2 1631.55
  5525.8 1632.58  5622.7 1632.64  5685.8 1633.21  5691.3 1633.91  5708.7 1633.71
  5714.2 1634.19  5721.2 1633.69  5737.0 1635.67  5743.2 1637.03  5759.8 1636.27
#Mann=3,-1,0
  4275.7    0.05       0  4965.2   0.035       0  4976.3    0.05       0
Bank Sta=4965.2,4976.3
Exp/Cntr=0.3,0.1

Type RM Length L Ch R = 1,13057,428,428,428
BEGIN DESCRIPTION:
Mapping XS 953c1a34
END DESCRIPTION:
XS GIS Cut Line= 2
      1593717.72      6911027.28      1592375.63      6910626.32
#Sta/Elev= 30
  4636.9 1644.16  4648.4 1643.37  4660.6 1641.01  4681.5 1638.32  4692.0 1636.04
  4712.8 1635.52  4744.1 1633.27  4838.0 1631.58  4857.6 1632.05  4936.8 1631.33
  4937.3 1630.83  4947.6 1630.83  4948.1 1631.33  5234.6 1631.72  5307.7 1632.54
  5352.6 1631.88  5424.0 1633.48  5457.2 1632.52  5547.7 1632.37  5579.0 1633.49
  5594.9 1632.97  5600.1 1633.73  5610.4 1633.04  5683.4 1632.54  5699.5 1633.54
  5765.7 1632.87  5842.4 1634.13  5996.5 1633.52  6027.8 1634.28  6037.6 1636.19
#Mann=3,-1,0
  4636.9    0.05       0  4936.8   0.035       0  4948.1    0.05       0
Bank Sta=4936.8,4948.1
Exp/Cntr=0.3,0.1

Type RM Length L Ch R = 1,12629,384,384,384
BEGIN DESCRIPTION:
Mapping XS 76aa7448
END DESCRIPTION:
XS GIS Cut Line= 2
      1593755.14      6910682.42      1592433.75      6910318.83
#Sta/Elev= 30
  4636.1 1635.95  4646.6 1635.31  4657.0 1635.33  4672.1 1635.81  4677.7 1637.43
  4688.1 1638.01  4698.5 1637.87  4719.2 1634.86  4760.7 1632.72  4791.8 1632.10
  4833.3 1632.39  4843.7 1632.01  4894.1 1631.98  4899.2 1632.31  4928.0 1631.82
  4928.5 1631.32  4938.8 1631.32  4939.3 1631.82  5092.6 1632.17  5248.2 1633.68
  5382.8 1633.28  5403.8 1633.85  5427.6 1633.82  5462.0 1633.33  5631.9 1632.90
  5797.6 1633.48  5950.7 1633.36  5984.6 1634.28  6003.3 1637.38  6006.6 1637.38
#Mann=3,-1,0
  4636.1    0.05       0  4928.0    0.05       0  4939.3    0.05       0
Bank Sta=4928,4939.3
Exp/Cntr=0.3,0.1

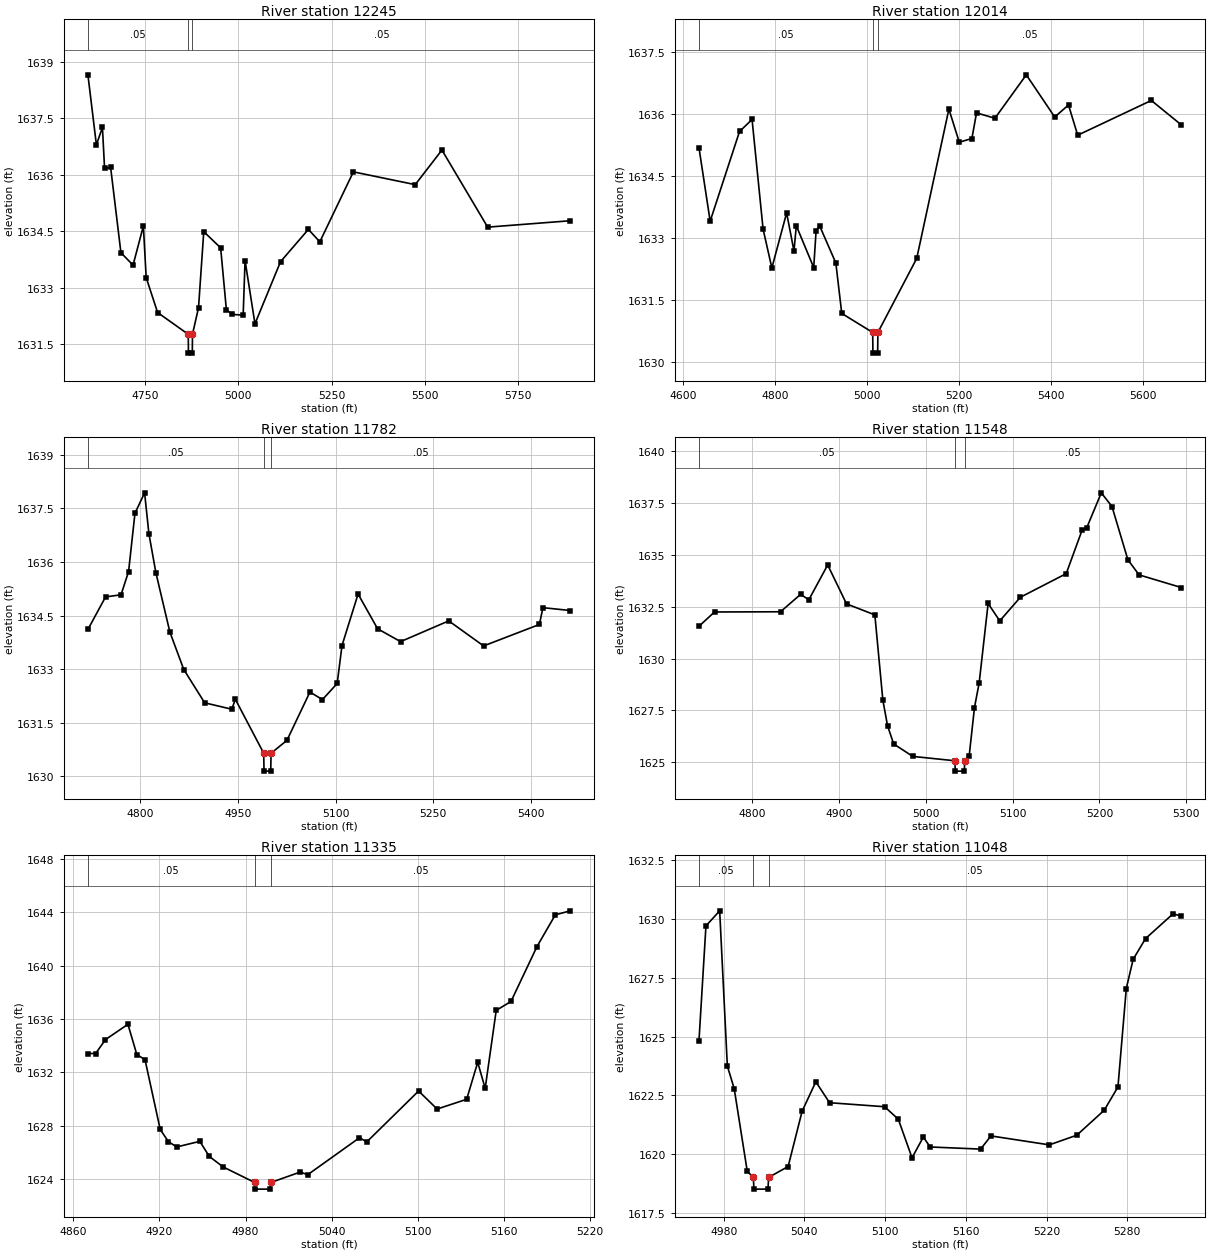
Type RM Length L Ch R = 1,12245,231,231,231
BEGIN DESCRIPTION:
Mapping XS df7a1830
END DESCRIPTION:
XS GIS Cut Line= 3
      1593782.40      6910442.43      1593508.37      6910295.18
      1592548.60      6910095.06
#Sta/Elev= 30
  4597.7 1638.66  4620.4 1636.80  4636.6 1637.26  4642.3 1636.17  4658.5 1636.20
  4686.1 1633.93  4718.6 1633.60  4746.2 1634.64  4753.7 1633.27  4784.3 1632.34
  4866.4 1631.76  4866.9 1631.26  4877.2 1631.26  4877.7 1631.76  4893.9 1632.47
  4907.9 1634.49  4953.1 1634.06  4968.4 1632.42  4983.7 1632.29  5013.4 1632.27
  5018.5 1633.72  5045.0 1632.04  5113.4 1633.69  5188.0 1634.55  5218.7 1634.22
  5308.5 1636.08  5474.1 1635.74  5545.6 1636.66  5668.1 1634.61  5889.2 1634.78
#Mann=3,-1,0
  4597.7    0.05       0  4866.4   0.035       0  4877.7    0.05       0
Bank Sta=4866.4,4877.7
Exp/Cntr=0.3,0.1

Type RM Length L Ch R = 1,12014,232,232,232
BEGIN DESCRIPTION:
Mapping XS 3a24eab8
END DESCRIPTION:
XS GIS Cut Line= 3
      1593781.24      6910179.00      1593475.73      6910109.56
      1592739.84      6910060.96
#Sta/Elev= 30
  4633.7 1635.19  4658.1 1633.41  4722.1 1635.58  4749.4 1635.87  4773.4 1633.22
  4792.5 1632.28  4824.7 1633.61  4840.7 1632.69  4845.8 1633.30  4883.7 1632.29
  4888.9 1633.18  4896.5 1633.30  4931.9 1632.40  4944.8 1631.18  5012.2 1630.72
  5012.7 1630.22  5023.0 1630.22  5023.5 1630.72  5108.1 1632.51  5178.2 1636.12
  5200.8 1635.32  5228.3 1635.41  5238.4 1636.03  5278.5 1635.90  5346.8 1636.95
  5408.7 1635.93  5438.8 1636.22  5458.8 1635.49  5619.2 1636.33  5684.5 1635.74
#Mann=3,-1,0
  4633.7    0.05       0  5012.2    0.03       0  5023.5    0.05       0
Bank Sta=5012.2,5023.5
Exp/Cntr=0.3,0.1

Type RM Length L Ch R = 1,11782,234,234,234
BEGIN DESCRIPTION:
Mapping XS 73fe12b7
END DESCRIPTION:
XS GIS Cut Line= 2
      1593632.49      6910023.82      1592940.73      6909757.92
#Sta/Elev= 30
  4719.3 1634.11  4746.4 1635.02  4770.2 1635.08  4781.8 1635.73  4791.6 1637.36
  4806.4 1637.93  4813.0 1636.79  4823.7 1635.70  4845.2 1634.04  4866.6 1632.99
  4898.7 1632.06  4940.4 1631.88  4945.8 1632.16  4989.4 1630.65  4989.9 1630.15
  5000.2 1630.15  5000.7 1630.65  5025.1 1631.01  5060.4 1632.36  5079.7 1632.15
  5102.3 1632.60  5109.7 1633.66  5134.4 1635.10  5164.4 1634.13  5199.7 1633.77
  5273.7 1634.35  5327.3 1633.65  5413.0 1634.25  5418.4 1634.72  5460.4 1634.64
#Mann=3,-1,0
  4719.3    0.05       0  4989.4    0.05       0  5000.7    0.05       0
Bank Sta=4989.4,5000.7
Exp/Cntr=0.3,0.1

Type RM Length L Ch R = 1,11548,213,213,213
BEGIN DESCRIPTION:
Mapping XS 5b4b156d
END DESCRIPTION:
XS GIS Cut Line= 2
      1593741.46      6909837.08      1593230.21      6909620.31
#Sta/Elev= 30
  4738.9 1631.56  4756.8 1632.25  4832.8 1632.26  4855.9 1633.10  4865.4 1632.84
  4887.1 1634.52  4908.8 1632.64  4941.4 1632.11  4950.6 1628.00  4956.0 1626.76
  4963.1 1625.88  4985.1 1625.28  5033.5 1625.07  5034.0 1624.57  5044.4 1624.57
  5044.9 1625.07  5050.0 1625.31  5056.1 1627.64  5061.5 1628.83  5071.8 1632.66
  5085.2 1631.82  5108.9 1632.96  5161.7 1634.10  5179.9 1636.19  5185.3 1636.31
  5202.1 1638.00  5214.4 1637.34  5232.7 1634.77  5245.6 1634.04  5294.2 1633.43
#Mann=3,-1,0
  4738.9    0.05       0  5033.5    0.05       0  5044.9    0.05       0
Bank Sta=5033.5,5044.9
Exp/Cntr=0.3,0.1

Type RM Length L Ch R = 1,11335,287,287,287
BEGIN DESCRIPTION:
Deadman 12 17.0
END DESCRIPTION:
XS GIS Cut Line= 3
      1593669.61      6909599.36      1593555.00      6909538.00
      1593354.95      6909487.99
#Sta/Elev= 30
  4870.1 1633.42  4875.5 1633.42  4882.3 1634.46  4898.0 1635.61  4904.2 1633.34
  4909.9 1632.96  4920.5 1627.73  4926.2 1626.82  4932.0 1626.42  4948.1 1626.84
  4954.7 1625.71  4964.4 1624.92  4986.3 1623.76  4986.8 1623.26  4997.2 1623.26
  4997.7 1623.76  5018.1 1624.54  5023.3 1624.34  5059.4 1627.11  5064.5 1626.80
  5100.6 1630.61  5113.5 1629.26  5134.1 1629.99  5141.8 1632.76  5147.0 1630.81
  5154.7 1636.65  5165.0 1637.32  5183.1 1641.43  5195.9 1643.81  5206.3 1644.11
#Mann=3,-1,0
  4870.1    0.05       0  4986.3    0.03       0  4997.7    0.05       0
Bank Sta=4986.3,4997.7
Exp/Cntr=0.3,0.1

Type RM Length L Ch R = 1,11048,165,165,165
BEGIN DESCRIPTION:
Mapping XS 05e89481
END DESCRIPTION:
XS GIS Cut Line= 2
      1593730.13      6909307.38      1593378.92      6909234.94
#Sta/Elev= 30
  4961.6 1624.81  4966.8 1629.70  4977.0 1630.34  4982.7 1623.75  4987.8 1622.79
  4997.5 1619.28  5002.0 1619.02  5002.5 1618.52  5012.9 1618.52  5013.4 1619.02
  5027.9 1619.48  5038.3 1621.83  5048.5 1623.08  5058.7 1622.19  5099.6 1622.02
  5109.8 1621.49  5120.0 1619.85  5128.4 1620.73  5133.5 1620.31  5171.0 1620.22
  5178.7 1620.78  5222.1 1620.40  5242.5 1620.81  5262.9 1621.87  5273.1 1622.86
  5279.3 1627.04  5284.4 1628.28  5293.6 1629.16  5314.0 1630.21  5320.2 1630.12
#Mann=3,-1,0
  4961.6    0.05       0  5002.0   0.035       0  5013.4    0.05       0
Bank Sta=5002,5013.4
Exp/Cntr=0.3,0.1

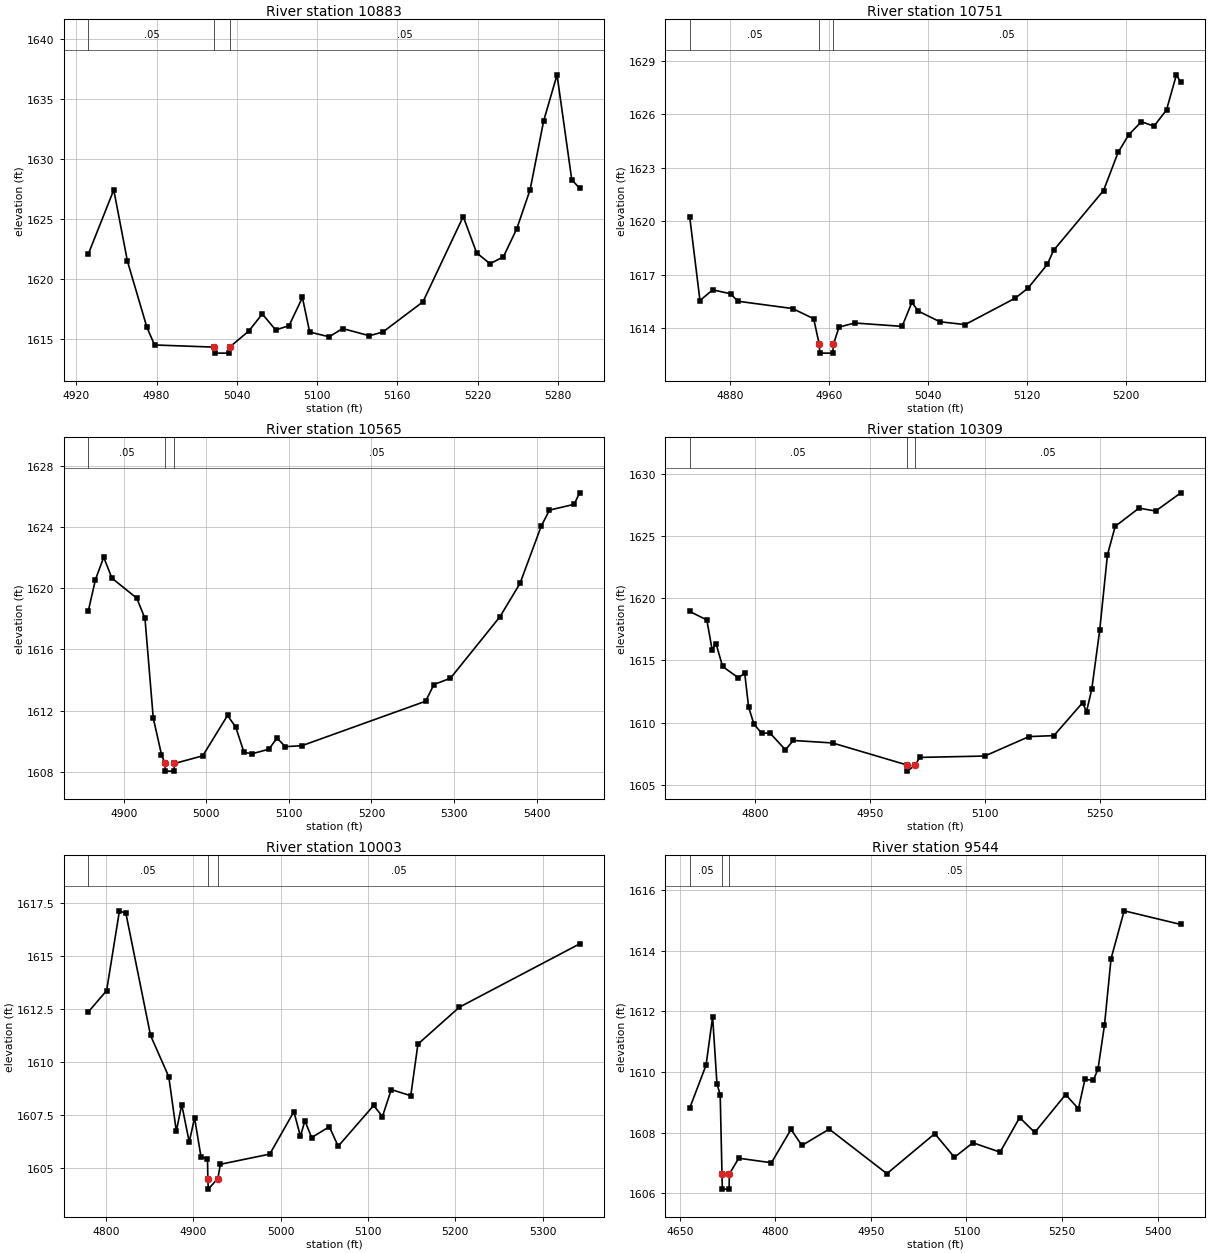
Type RM Length L Ch R = 1,10883,132,132,132
BEGIN DESCRIPTION:
Deadman 12 16.0
END DESCRIPTION:
XS GIS Cut Line= 3
      1593773.65      6909151.05      1593705.00      6909138.00
      1593408.19      6909122.49
#Sta/Elev= 30
  4929.0 1622.09  4948.0 1627.43  4958.2 1621.49  4972.8 1615.96  4978.5 1614.50
  5023.2 1614.32  5023.7 1613.82  5034.1 1613.82  5034.6 1614.32  5048.9 1615.66
  5059.0 1617.09  5069.0 1615.75  5079.0 1616.11  5089.0 1618.46  5094.4 1615.58
  5109.0 1615.18  5119.0 1615.87  5139.1 1615.27  5149.1 1615.58  5179.1 1618.10
  5209.2 1625.21  5219.2 1622.18  5229.2 1621.28  5239.2 1621.85  5249.2 1624.19
  5259.2 1627.46  5269.3 1633.19  5279.3 1637.03  5290.3 1628.28  5296.1 1627.58
#Mann=3,-1,0
  4929.0    0.05       0  5023.2   0.035       0  5034.6    0.05       0
Bank Sta=5023.2,5034.6
Exp/Cntr=0.3,0.1

Type RM Length L Ch R = 1,10751,186,186,186
BEGIN DESCRIPTION:
Mapping XS 1f1a70a3
END DESCRIPTION:
XS GIS Cut Line= 3
      1593773.17      6909026.51      1593624.74      6909057.22
      1593383.65      6909103.14
#Sta/Elev= 30
  4847.5 1620.24  4855.8 1615.54  4866.1 1616.14  4880.5 1615.92  4886.5 1615.50
  4930.7 1615.09  4947.7 1614.52  4952.2 1613.09  4952.7 1612.59  4963.2 1612.59
  4963.7 1613.09  4968.2 1614.05  4980.9 1614.28  5019.2 1614.09  5027.1 1615.44
  5032.2 1614.95  5049.7 1614.35  5070.1 1614.19  5110.8 1615.68  5121.0 1616.24
  5136.6 1617.57  5141.6 1618.35  5182.0 1621.71  5193.8 1623.85  5202.4 1624.84
  5212.6 1625.57  5222.8 1625.32  5232.9 1626.23  5240.9 1628.20  5244.5 1627.77
#Mann=3,-1,0
  4847.5    0.05       0  4952.2   0.035       0  4963.7    0.05       0
Bank Sta=4952.2,4963.7
Exp/Cntr=0.3,0.1

Type RM Length L Ch R = 1,10565,256,256,256
BEGIN DESCRIPTION:
Mapping XS 65997941
END DESCRIPTION:
XS GIS Cut Line= 2
      1593833.59      6908898.44      1593238.61      6908903.64
#Sta/Elev= 30
  4857.0 1618.52  4865.6 1620.56  4875.6 1622.02  4885.6 1620.65  4915.6 1619.35
  4925.6 1618.02  4935.6 1611.52  4945.6 1609.12  4949.8 1608.54  4950.3 1608.04
  4960.8 1608.04  4961.3 1608.54  4995.6 1609.04  5025.6 1611.68  5035.6 1610.91
  5045.6 1609.26  5055.6 1609.18  5075.6 1609.47  5085.6 1610.20  5095.6 1609.64
  5115.6 1609.70  5265.6 1612.61  5275.6 1613.70  5295.6 1614.11  5355.6 1618.13
  5379.9 1620.31  5405.6 1624.05  5415.6 1625.10  5445.6 1625.48  5452.0 1626.23
#Mann=3,-1,0
  4857.0    0.05       0  4949.8   0.035       0  4961.3    0.05       0
Bank Sta=4949.8,4961.3
Exp/Cntr=0.3,0.1

Type RM Length L Ch R = 1,10309,306,306,306
BEGIN DESCRIPTION:
Mapping XS 66656923
END DESCRIPTION:
XS GIS Cut Line= 2
      1593846.85      6908790.01      1593221.61      6908644.71
#Sta/Elev= 30
  4714.3 1618.93  4736.7 1618.25  4743.6 1615.87  4748.7 1616.35  4757.3 1614.52
  4777.8 1613.61  4786.2 1613.98  4791.3 1611.25  4798.3 1609.89  4808.6 1609.14
  4818.9 1609.20  4839.4 1607.83  4849.7 1608.58  4901.0 1608.38  4997.9 1606.62
  4998.4 1606.12  5009.4 1606.62  5014.7 1607.22  5099.9 1607.33  5157.7 1608.89
  5190.3 1608.97  5227.8 1611.61  5232.9 1610.89  5239.8 1612.71  5250.1 1617.41
  5260.3 1623.49  5270.4 1625.76  5301.4 1627.22  5323.3 1626.99  5356.2 1628.45
#Mann=3,-1,0
  4714.3    0.05       0  4997.9   0.035       0  5009.4    0.05       0
Bank Sta=4997.9,5009.4
Exp/Cntr=0.3,0.1

Type RM Length L Ch R = 1,10003,459,459,459
BEGIN DESCRIPTION:
Deadman 12 15.0
END DESCRIPTION:
XS GIS Cut Line= 3
      1593929.98      6908612.98      1593755.00      6908488.00
      1593412.52      6908430.51
#Sta/Elev= 30
  4780.0 1612.35  4800.9 1613.35  4815.6 1617.11  4823.0 1616.99  4851.2 1611.24
  4872.1 1609.29  4880.7 1606.73  4886.9 1607.98  4895.5 1606.22  4901.6 1607.36
  4909.0 1605.51  4916.4 1605.44  4916.8 1604.50  4917.3 1604.00  4928.3 1604.50
  4931.1 1605.17  4987.7 1605.65  5015.3 1607.65  5022.8 1606.49  5027.9 1607.22
  5035.6 1606.43  5055.9 1606.94  5066.0 1606.02  5106.6 1607.94  5116.7 1607.42
  5126.8 1608.69  5149.1 1608.40  5157.3 1610.83  5204.7 1612.57  5342.3 1615.55
#Mann=3,-1,0
  4780.0    0.05       0  4916.8   0.035       0  4928.3    0.05       0
Bank Sta=4916.8,4928.3
Exp/Cntr=0.3,0.1

Type RM Length L Ch R = 1,9544,566,566,566
BEGIN DESCRIPTION:
Deadman 12 14.0
END DESCRIPTION:
XS GIS Cut Line= 3
      1594030.04      6908213.01      1593705.00      6908138.00
      1593278.04      6908233.50
#Sta/Elev= 30
  4665.5 1608.81  4691.2 1610.23  4701.5 1611.82  4708.3 1609.62  4713.4 1609.25
  4716.2 1606.64  4716.7 1606.14  4727.3 1606.14  4727.8 1606.64  4742.5 1607.16
  4793.8 1607.01  4824.6 1608.11  4841.7 1607.58  4884.5 1608.12  4975.1 1606.65
  5050.3 1607.97  5081.1 1607.19  5110.1 1607.67  5152.8 1607.36  5183.5 1608.50
  5207.2 1608.01  5255.7 1609.26  5275.8 1608.79  5286.0 1609.76  5299.1 1609.73
  5306.5 1610.10  5316.7 1611.55  5327.0 1613.74  5347.6 1615.32  5436.6 1614.87
#Mann=3,-1,0
  4665.5    0.05       0  4716.2    0.05       0  4727.8    0.05       0
Bank Sta=4716.2,4727.8
Exp/Cntr=0.3,0.1

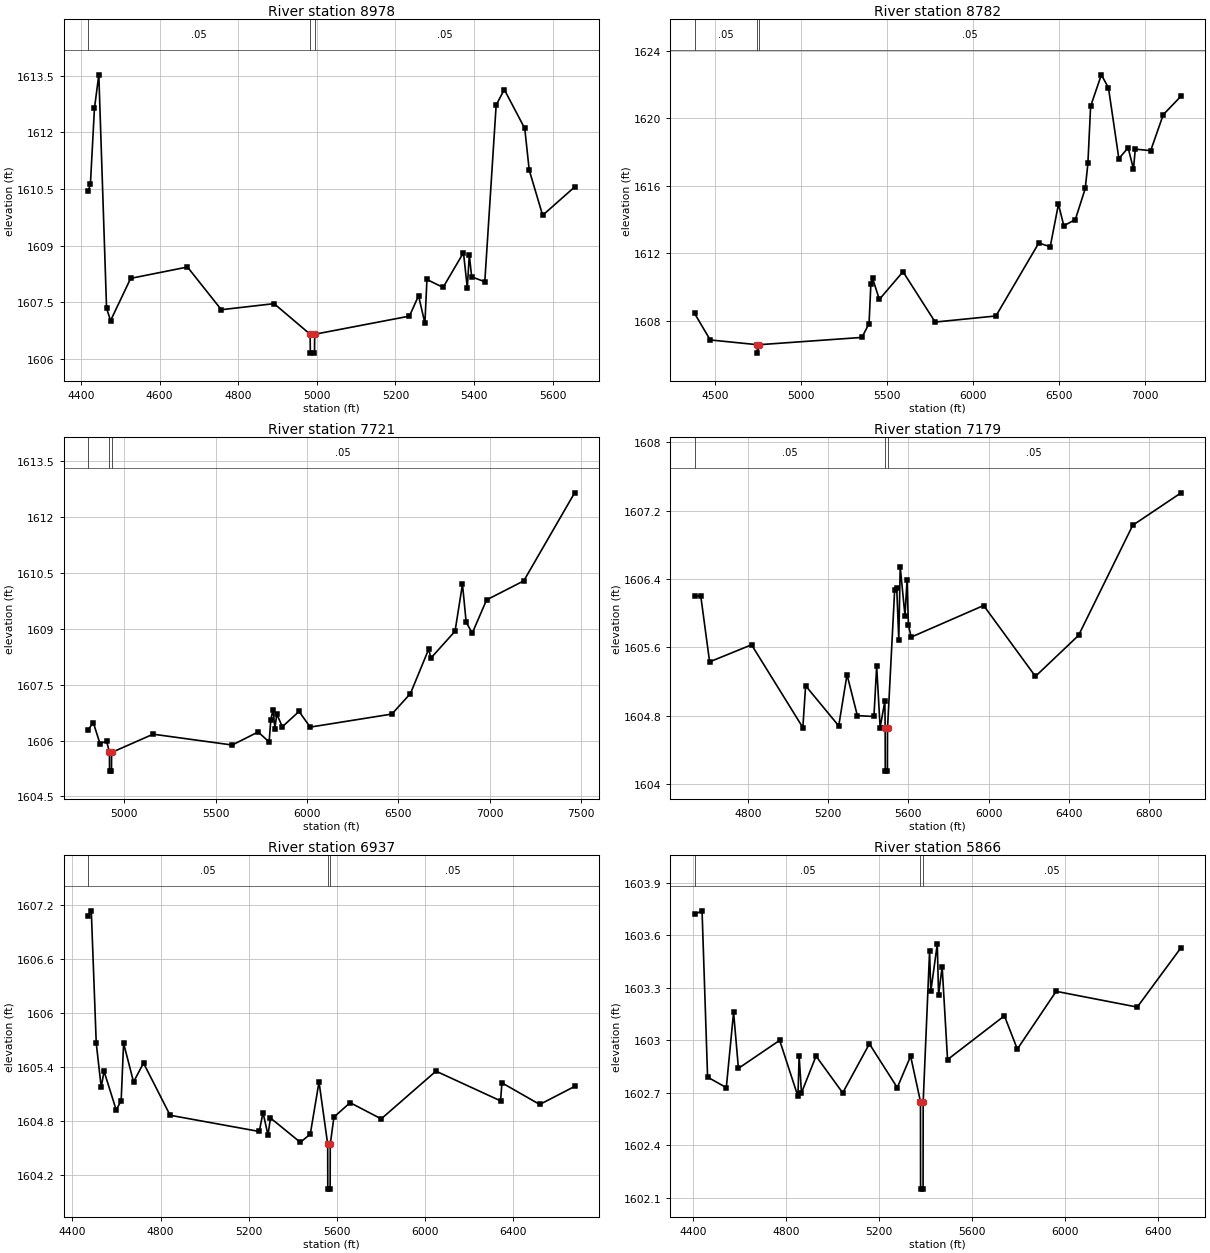
Type RM Length L Ch R = 1,8978,196,196,196
BEGIN DESCRIPTION:
Deadman 12 13.0
END DESCRIPTION:
XS GIS Cut Line= 3
      1594120.68      6907788.11      1593594.66      6907668.32
      1592922.82      6907480.83
#Sta/Elev= 30
  4418.5 1610.44  4424.3 1610.62  4434.6 1612.63  4445.7 1613.52  4465.4 1607.34
  4475.6 1607.01  4526.7 1608.13  4671.1 1608.43  4757.2 1607.30  4891.4 1607.46
  4983.0 1606.65  4983.5 1606.15  4994.1 1606.15  4994.6 1606.65  5235.5 1607.13
  5258.7 1607.67  5274.8 1606.94  5280.0 1608.10  5321.0 1607.89  5372.9 1608.81
  5382.6 1607.88  5387.7 1608.75  5393.7 1608.17  5427.1 1608.04  5456.0 1612.72
  5476.7 1613.13  5528.7 1612.10  5540.0 1611.00  5574.2 1609.80  5655.5 1610.55
#Mann=3,-1,0
  4418.5    0.05       0  4983.0    0.05       0  4994.6    0.05       0
Bank Sta=4983,4994.6
Exp/Cntr=0.3,0.1

Type RM Length L Ch R = 1,8782,1061,1061,1061
BEGIN DESCRIPTION:
Mapping XS e1ae8206
END DESCRIPTION:
XS GIS Cut Line= 3
      1594151.60      6907656.66      1593133.03      6907368.06
      1591428.59      6906885.14
#Sta/Elev= 30
  4379.0 1608.44  4470.0 1606.87  4743.8 1606.59  4744.3 1606.09  4755.4 1606.59
  5352.5 1607.02  5394.0 1607.84  5404.4 1610.16  5414.6 1610.52  5453.7 1609.27
  5591.5 1610.91  5778.6 1607.93  6132.0 1608.29  6381.4 1612.61  6447.8 1612.39
  6495.8 1614.91  6527.0 1613.63  6594.0 1614.00  6651.7 1615.84  6667.0 1617.32
  6682.9 1620.71  6745.3 1622.57  6786.8 1621.80  6847.1 1617.61  6901.1 1618.25
  6932.3 1616.99  6942.7 1618.17  7032.3 1618.08  7105.4 1620.21  7209.2 1621.31
#Mann=3,-1,0
  4379.0    0.05       0  4743.8   0.035       0  4755.4    0.05       0
Bank Sta=4743.8,4755.4
Exp/Cntr=0.3,0.1

Type RM Length L Ch R = 1,7721,542,542,542
BEGIN DESCRIPTION:
Deadman 12 12.0
END DESCRIPTION:
XS GIS Cut Line= 4
      1594281.67      6907099.59      1594105.00      6906988.00
      1593324.00      6906851.57      1591691.01      6906566.30
#Sta/Elev= 30
  4803.5 1606.29  4831.8 1606.48  4868.3 1605.92  4904.8 1605.98  4920.1 1605.68
  4920.6 1605.18  4931.3 1605.18  4931.8 1605.68  5158.7 1606.17  5591.1 1605.88
  5733.2 1606.23  5793.0 1605.96  5802.2 1606.56  5814.4 1606.83  5824.6 1606.32
  5834.7 1606.71  5865.2 1606.37  5956.5 1606.78  6017.4 1606.36  6464.1 1606.71
  6565.6 1607.26  6665.3 1608.45  6677.3 1608.21  6809.3 1608.93  6849.9 1610.19
  6870.2 1609.17  6903.4 1608.88  6981.8 1609.77  7184.9 1610.28  7463.0 1612.64
#Mann=3,-1,0
  4803.5    0.05       0  4920.1   0.035       0  4931.8    0.05       0
Bank Sta=4920.1,4931.8
Exp/Cntr=0.3,0.1

Type RM Length L Ch R = 1,7179,242,242,242
BEGIN DESCRIPTION:
Mapping XS 7089132f
END DESCRIPTION:
XS GIS Cut Line= 4
      1594341.00      6906845.44      1594022.78      6906677.95
      1593376.08      6906513.02      1592021.45      6906167.55
#Sta/Elev= 30
  4534.2 1606.20  4565.1 1606.20  4609.1 1605.43  4818.2 1605.63  5073.9 1604.66
  5087.6 1605.15  5252.7 1604.68  5294.0 1605.28  5345.6 1604.80  5428.2 1604.79
  5441.8 1605.38  5459.1 1604.66  5482.6 1604.97  5484.2 1604.65  5484.7 1604.15
  5495.4 1604.15  5495.9 1604.65  5531.4 1606.27  5541.7 1606.30  5552.0 1605.69
  5559.2 1606.54  5583.0 1605.97  5593.3 1606.39  5600.1 1605.86  5613.9 1605.72
  5975.1 1606.09  6233.1 1605.26  6448.1 1605.74  6718.2 1607.03  6959.2 1607.41
#Mann=3,-1,0
  4534.2    0.05       0  5484.2   0.035       0  5495.9    0.05       0
Bank Sta=5484.2,5495.9
Exp/Cntr=0.3,0.1

Type RM Length L Ch R = 1,6937,1071,1071,1071
BEGIN DESCRIPTION:
Mapping XS ae1d9f10
END DESCRIPTION:
XS GIS Cut Line= 4
      1594379.17      6906681.91      1594374.35      6906677.95
      1593324.00      6906170.14      1592392.37      6905719.73
#Sta/Elev= 30
  4471.2 1607.07  4485.6 1607.13  4508.1 1605.66  4530.7 1605.17  4543.4 1605.35
  4598.5 1604.92  4621.1 1605.02  4632.2 1605.66  4677.4 1605.23  4722.6 1605.44
  4843.3 1604.86  5247.8 1604.68  5264.9 1604.89  5287.5 1604.64  5298.7 1604.83
  5434.1 1604.56  5479.3 1604.65  5519.0 1605.23  5558.3 1604.54  5558.8 1604.04
  5569.5 1604.04  5570.0 1604.54  5586.7 1604.84  5660.1 1605.00  5801.2 1604.82
  6049.7 1605.35  6342.8 1605.02  6349.0 1605.22  6520.5 1604.98  6678.9 1605.18
#Mann=3,-1,0
  4471.2    0.05       0  5558.3   0.035       0  5570.0    0.05       0
Bank Sta=5558.3,5570
Exp/Cntr=0.3,0.1

Type RM Length L Ch R = 1,5866,226,226,226
BEGIN DESCRIPTION:
Mapping XS e77193d9
END DESCRIPTION:
XS GIS Cut Line= 2
      1594635.79      6905708.09      1592629.75      6905119.85
#Sta/Elev= 30
  4407.1 1603.72  4439.2 1603.74  4463.0 1602.79  4543.4 1602.73  4574.7 1603.16
  4595.5 1602.84  4772.7 1603.00  4851.2 1602.68  4856.4 1602.91  4866.4 1602.70
  4929.0 1602.91  5043.6 1602.70  5158.2 1602.98  5278.1 1602.73  5335.4 1602.91
  5377.7 1602.65  5378.2 1602.15  5388.9 1602.15  5389.4 1602.65  5416.9 1603.51
  5422.1 1603.28  5450.0 1603.55  5455.5 1603.26  5470.9 1603.42  5494.1 1602.89
  5738.4 1603.14  5793.9 1602.95  5960.7 1603.28  6309.2 1603.19  6497.6 1603.53
#Mann=3,-1,0
  4407.1    0.05       0  5377.7    0.03       0  5389.4    0.05       0
Bank Sta=5377.7,5389.4
Exp/Cntr=0.3,0.1