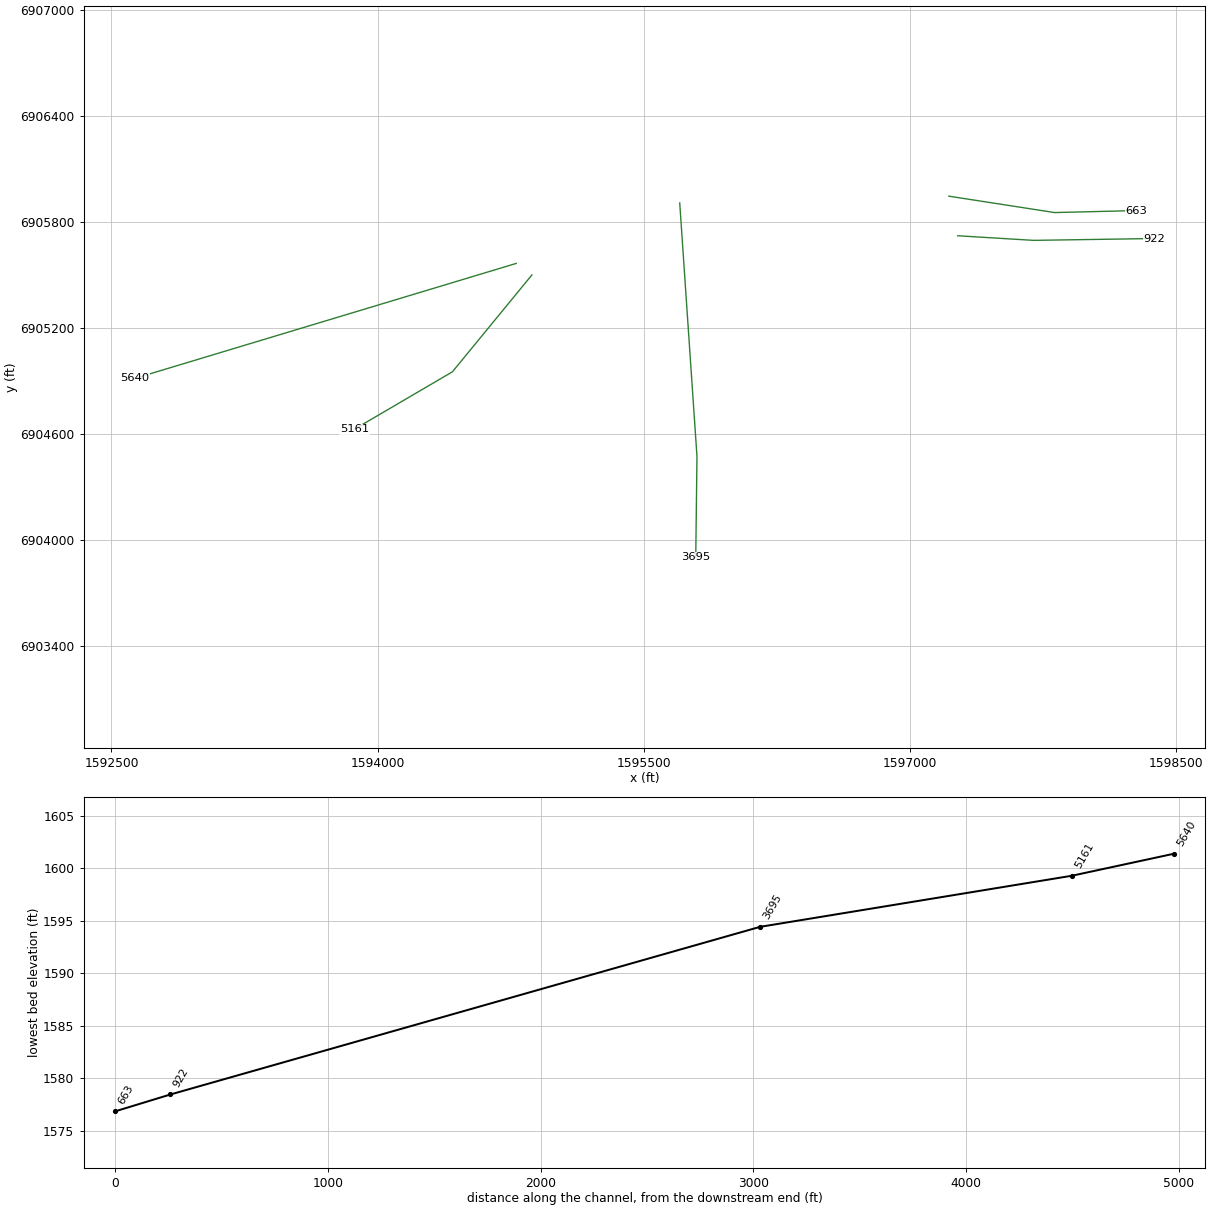
HEC-RAS study Deadman 12.prj: Deadman 12 Base Level Engineering

--- Deadman 12.g01 (geometry) --- (continued)

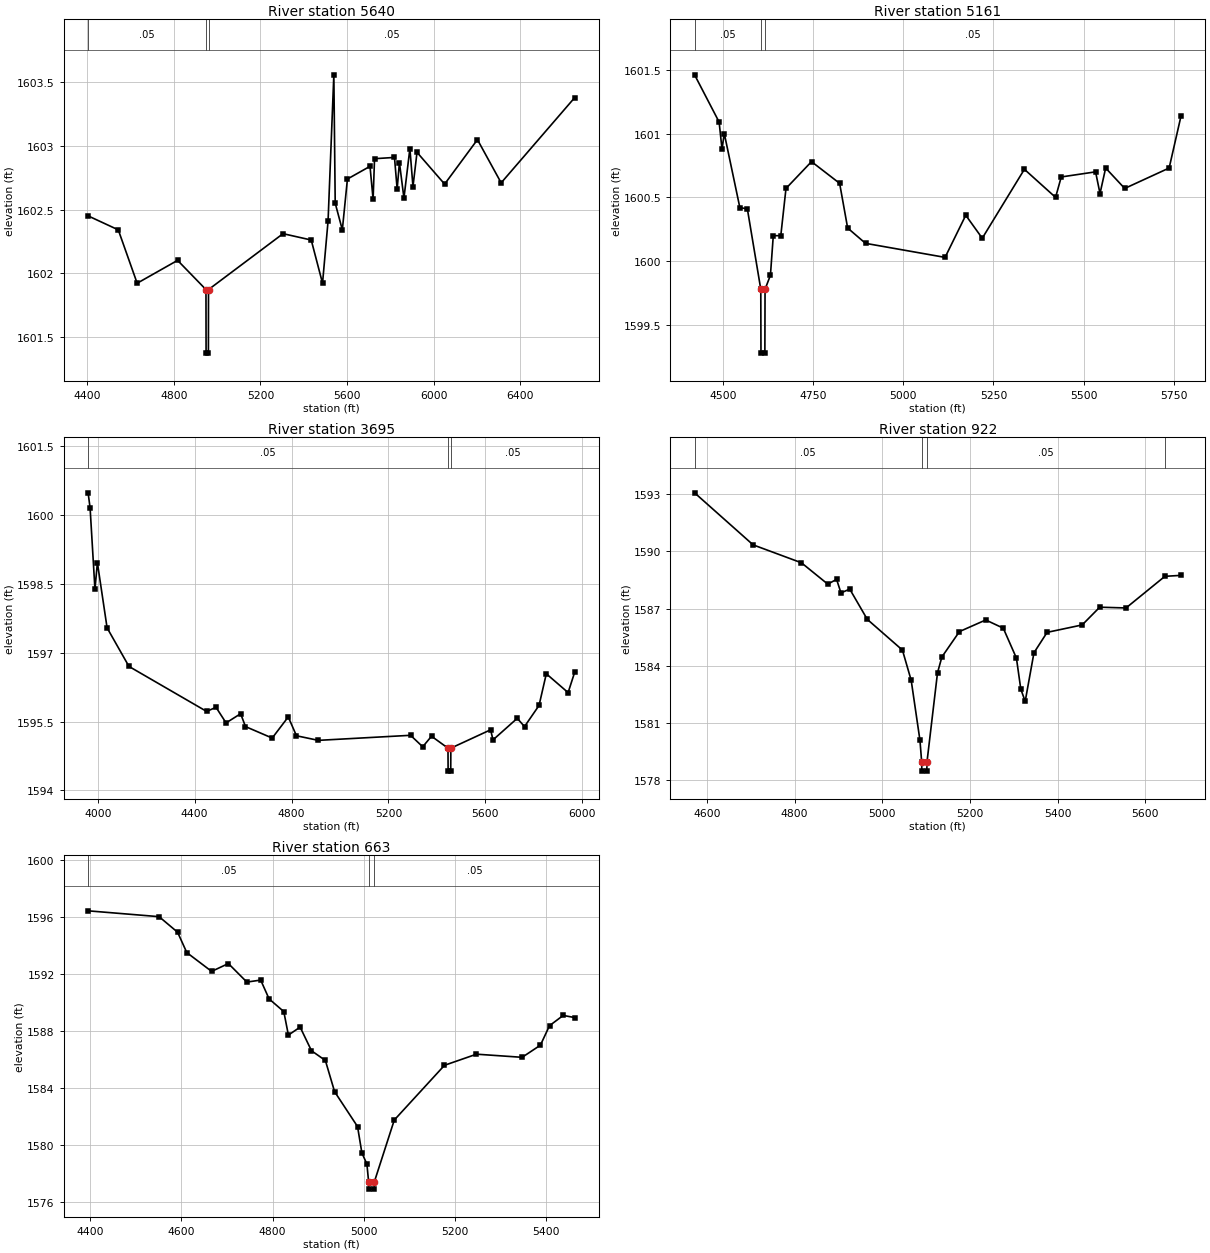
Type RM Length L Ch R = 1,5640,479,479,479
BEGIN DESCRIPTION:
Mapping XS 01b0a0d0
END DESCRIPTION:
XS GIS Cut Line= 2
      1594781.86      6905563.86      1592630.03      6904913.01
#Sta/Elev= 30
  4403.6 1602.45  4543.0 1602.34  4630.2 1601.92  4817.0 1602.10  4948.2 1601.87
  4948.7 1601.37  4959.4 1601.37  4959.9 1601.87  5304.3 1602.31  5434.6 1602.26
  5486.8 1601.92  5512.4 1602.41  5539.1 1603.56  5545.4 1602.55  5578.3 1602.34
  5601.8 1602.74  5706.2 1602.84  5720.5 1602.58  5727.1 1602.90  5819.3 1602.91
  5831.6 1602.66  5842.1 1602.87  5863.0 1602.59  5890.5 1602.98  5904.7 1602.68
  5923.4 1602.95  6051.0 1602.70  6202.6 1603.05  6312.2 1602.71  6651.7 1603.38
#Mann=3,-1,0
  4403.6    0.05       0  4948.2    0.03       0  4959.9    0.05       0
Bank Sta=4948.2,4959.9
Exp/Cntr=0.3,0.1

Type RM Length L Ch R = 1,5161,1466,1466,1466
BEGIN DESCRIPTION:
Mapping XS 292549f0
END DESCRIPTION:
XS GIS Cut Line= 3
      1594870.56      6905498.65      1594422.09      6904950.52
      1593870.69      6904626.64
#Sta/Elev= 30
  4422.1 1601.46  4490.1 1601.09  4498.0 1600.88  4504.4 1601.00  4547.5 1600.42
  4568.3 1600.41  4605.5 1599.78  4606.0 1599.28  4616.8 1599.28  4617.3 1599.78
  4632.2 1599.89  4640.1 1600.20  4660.9 1600.20  4675.3 1600.57  4746.0 1600.78
  4823.9 1600.61  4846.1 1600.26  4895.6 1600.14  5116.0 1600.03  5173.3 1600.36
  5219.0 1600.18  5335.7 1600.72  5422.1 1600.50  5437.8 1600.66  5532.9 1600.70
  5545.2 1600.53  5560.8 1600.73  5613.6 1600.57  5736.7 1600.73  5769.8 1601.14
#Mann=3,-1,0
  4422.1    0.05       0  4605.5   0.035       0  4617.3    0.05       0
Bank Sta=4605.5,4617.3
Exp/Cntr=0.3,0.1

Type RM Length L Ch R = 1,3695,2773,2773,2773
BEGIN DESCRIPTION:
Mapping XS 9c4921c7
END DESCRIPTION:
XS GIS Cut Line= 3
      1595704.04      6905906.16      1595801.26      6904472.14
      1595794.34      6903901.10
#Sta/Elev= 30
  3960.1 1600.48  3968.3 1600.15  3988.3 1598.38  3998.4 1598.96  4038.4 1597.54
  4128.7 1596.70  4449.4 1595.72  4488.1 1595.81  4529.6 1595.47  4589.7 1595.67
  4609.8 1595.39  4720.0 1595.14  4786.3 1595.60  4820.2 1595.19  4910.4 1595.09
  5291.3 1595.20  5341.4 1594.95  5377.7 1595.18  5445.7 1594.92  5446.2 1594.42
  5457.0 1594.42  5457.5 1594.92  5621.6 1595.32  5631.6 1595.10  5731.6 1595.57
  5761.6 1595.39  5821.6 1595.85  5851.6 1596.54  5941.6 1596.13  5968.5 1596.57
#Mann=3,-1,0
  3960.1    0.05       0  5445.7   0.035       0  5457.5    0.05       0
Bank Sta=5445.7,5457.5
Exp/Cntr=0.3,0.1

Type RM Length L Ch R = 1,922,259,259,259
BEGIN DESCRIPTION:
Mapping XS b86ac3d5
END DESCRIPTION:
XS GIS Cut Line= 3
      1597271.72      6905720.40      1597698.83      6905694.36
      1598380.54      6905704.77
#Sta/Elev= 30
  4572.0 1593.07  4705.5 1590.34  4815.7 1589.40  4875.8 1588.28  4895.9 1588.53
  4905.9 1587.82  4925.9 1588.02  4966.0 1586.43  5046.1 1584.82  5066.1 1583.23
  5086.1 1580.08  5089.9 1578.97  5090.4 1578.47  5101.7 1578.47  5102.2 1578.97
  5126.1 1583.63  5136.1 1584.46  5176.1 1585.79  5236.1 1586.40  5276.1 1585.97
  5306.1 1584.40  5316.1 1582.77  5326.1 1582.13  5346.1 1584.68  5376.1 1585.75
  5456.1 1586.14  5496.1 1587.07  5556.1 1587.03  5644.8 1588.69  5681.7 1588.74
#Mann=4,-1,0
  4572.0    0.05       0  5089.9    0.03       0  5102.2    0.05       0
  5644.8    0.12       0
Bank Sta=5089.9,5102.2
Exp/Cntr=0.3,0.1

Type RM Length L Ch R = 1,663,0,0,0
BEGIN DESCRIPTION:
Mapping XS 8628b3b0
END DESCRIPTION:
XS GIS Cut Line= 3
      1597221.37      6905944.36      1597818.21      6905851.63
      1598279.97      6905863.00
#Sta/Elev= 30
  4396.0 1596.40  4551.5 1595.99  4592.0 1594.90  4612.2 1593.47  4666.6 1592.15
  4703.3 1592.70  4743.8 1591.40  4774.1 1591.54  4792.5 1590.22  4824.7 1589.33
  4834.8 1587.68  4860.5 1588.24  4885.4 1586.58  4915.8 1585.90  4936.0 1583.71
  4986.3 1581.26  4995.8 1579.41  5006.8 1578.63  5010.6 1577.37  5011.1 1576.87
  5022.5 1576.87  5023.0 1577.37  5066.8 1581.72  5176.8 1585.56  5246.9 1586.34
  5346.9 1586.12  5386.9 1586.97  5406.9 1588.34  5436.9 1589.06  5461.9 1588.91
#Mann=3,-1,0
  4396.0    0.05       0  5010.6    0.03       0  5023.0    0.05       0
Bank Sta=5010.6,5023
Exp/Cntr=0.3,0.1

Chan Stop Cuts=-1