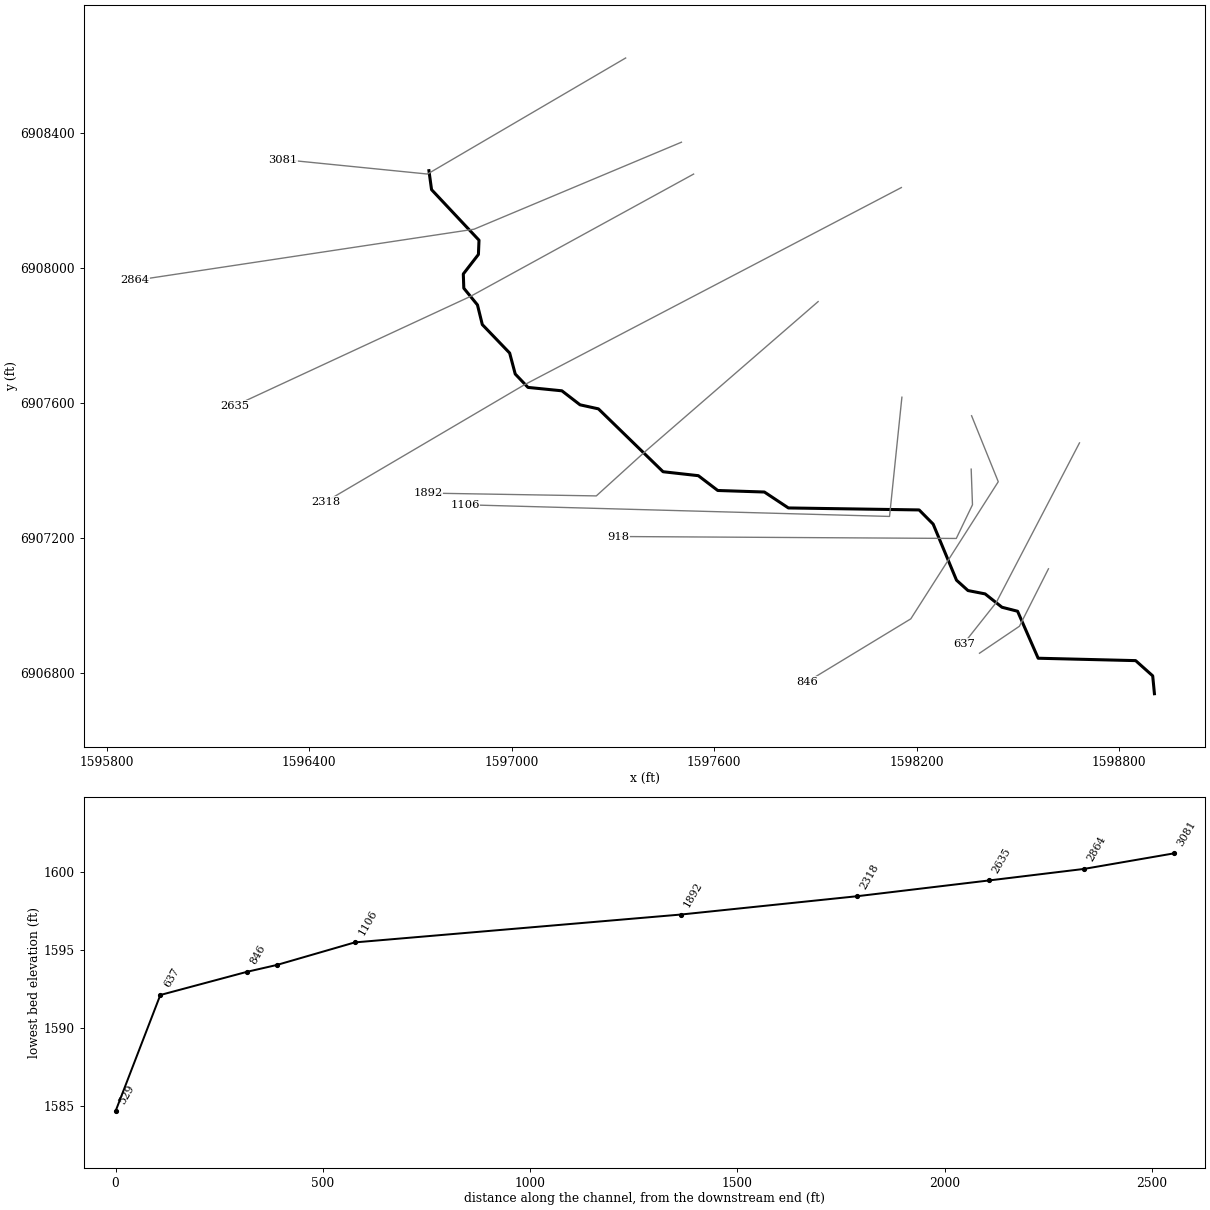
--- Deadman 13.prj (project) ---

Proj Title=Deadman 13 Base Level Engineering
Current Plan=p01
Default Exp/Contr=0.3,0.1
English Units
Geom File=g01
Flow File=f01
Plan File=p01
BEGIN DESCRIPTION:
Deadman 13
END DESCRIPTION:

--- Deadman 13.p01 (plan) ---

Plan Title=Multiple Run
Short Identifier=Multiple
Geom File=g01
Flow File=f01
Subcritical Flow
K Sum by GR= 0
Std Step Tol= 0.01
Critical Tol= 0.01
Num of Std Step Trials= 20
Max Error Tol= 0.3
Flow Tol Ratio= 0.001
Split Flow NTrial= 30
Split Flow Tol= 0.02
Split Flow Ratio= 0.02
Log Output Level= 0
Friction Slope Method= 1
Unsteady Friction Slope Method= 2
Unsteady Bridges Friction Slope Method= 1
Parabolic Critical Depth
Global Vel Dist=  1 , 1 , 1
Global Log Level= 0
CheckData=True
Encroach Param= -1, 0, 0, 0
BEGIN DESCRIPTION:
Multiple Run
END DESCRIPTION:

--- Deadman 13.f01 (steady flow) ---

Flow Title=Multiple
Number of Profiles=7
Profile Names=10-year,25-year,50-year,1pct_min,100-year,1pct_plu,500-year
River Rch & RM= Deadman 13,Reach-1,3081
     130     170     201     118     236     472     330
River Rch & RM= Deadman 13,Reach-1,2864
     182     244     292     175     348     695     501
Boundary for River Rch & Prof#=Deadman 13,Reach-1,1
Up Type=0
Dn Type=3
Dn Slope=0.005
Boundary for River Rch & Prof#=Deadman 13,Reach-1,2
Up Type=0
Dn Type=3
Dn Slope=0.005
Boundary for River Rch & Prof#=Deadman 13,Reach-1,3
Up Type=0
Dn Type=3
Dn Slope=0.005
Boundary for River Rch & Prof#=Deadman 13,Reach-1,4
Up Type=0
Dn Type=3
Dn Slope=0.005
Boundary for River Rch & Prof#=Deadman 13,Reach-1,5
Up Type=0
Dn Type=3
Dn Slope=0.005
Boundary for River Rch & Prof#=Deadman 13,Reach-1,6
Up Type=0
Dn Type=3
Dn Slope=0.005
Boundary for River Rch & Prof#=Deadman 13,Reach-1,7
Up Type=0
Dn Type=3
Dn Slope=0.005

--- Deadman 13.g01 (geometry) ---

Geom Title=Existing Conditions

River Reach=Deadman 13,Reach-1
Reach XY= 30
      1596755.00      6908288.00      1596762.76      6908231.79
      1596903.38      6908081.97      1596901.63      6908039.74
      1596856.84      6907981.89      1596858.34      6907939.72
      1596898.82      6907890.19      1596913.15      6907831.95
      1596994.19      6907747.65      1597010.74      6907685.43
      1597048.55      6907645.74      1597149.03      6907635.66
      1597202.83      6907594.14      1597257.30      6907582.17
      1597448.83      6907395.86      1597553.40      6907384.14
      1597610.94      6907340.27      1597749.06      6907335.73
      1597820.22      6907288.52      1598207.70      6907282.64
      1598249.29      6907240.58      1598318.47      6907074.43
      1598352.46      6907043.73      1598403.26      6907033.81
      1598453.15      6906994.24      1598499.42      6906982.42
      1598560.41      6906843.17      1598849.31      6906836.07
      1598899.87      6906790.95      1598905.00      6906738.00

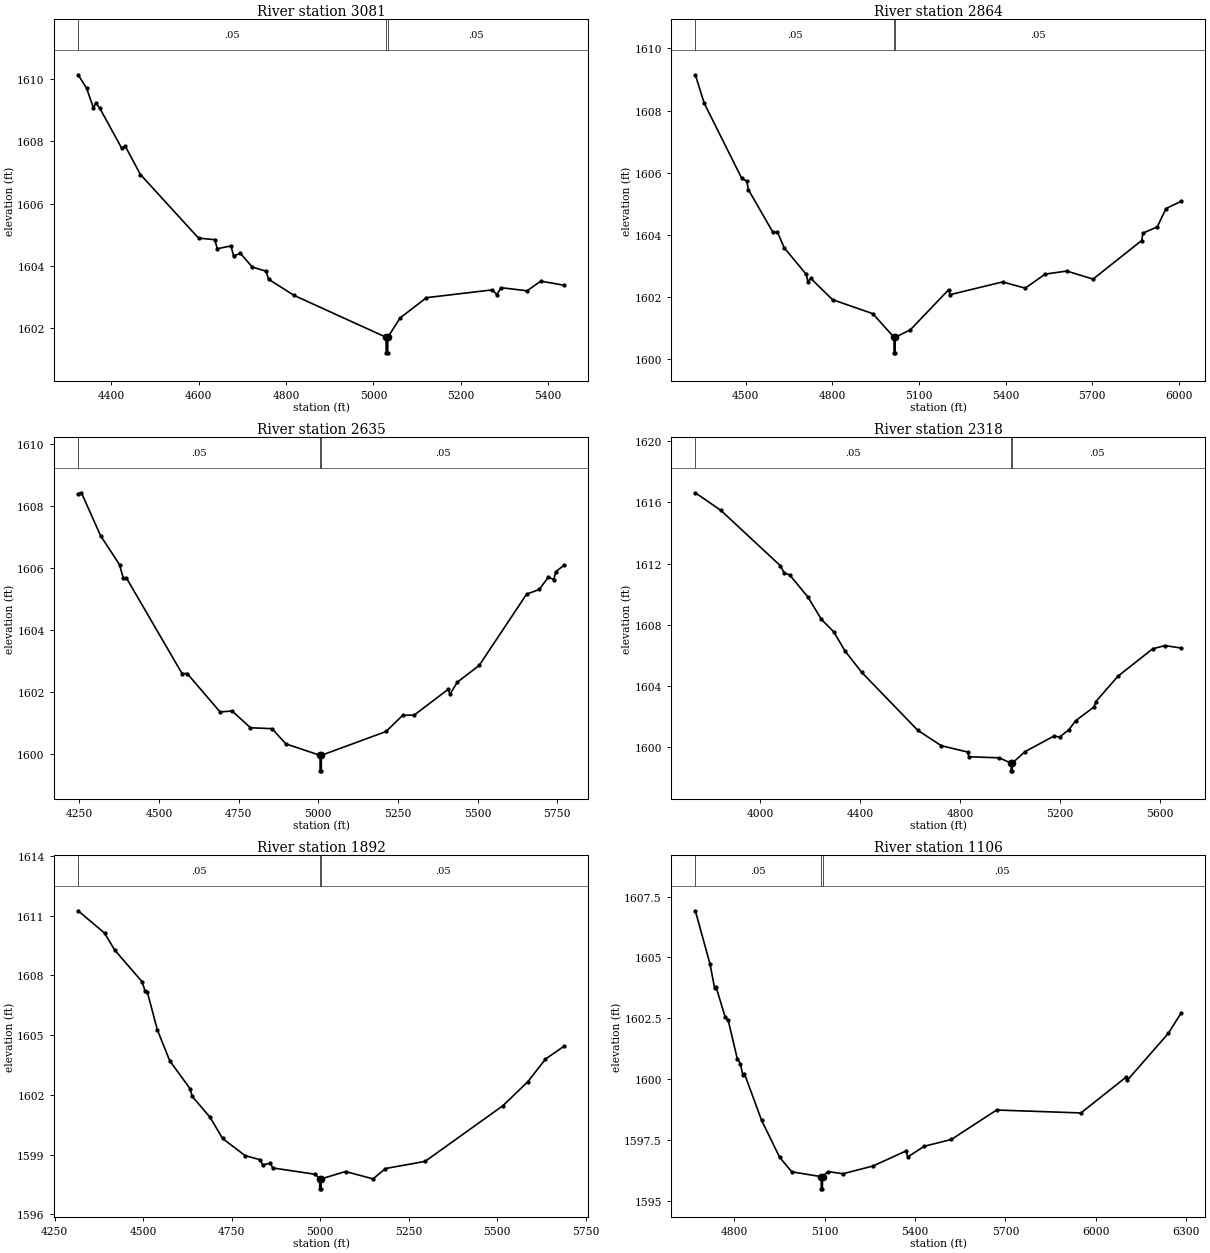
Type RM Length L Ch R = 1,3081,217,217,217
BEGIN DESCRIPTION:
Deadman 13 3.0
END DESCRIPTION:
XS GIS Cut Line= 3
      1597337.94      6908621.96      1596750.65      6908278.05
      1596322.17      6908320.99
#Sta/Elev= 30
  4324.6 1610.13  4343.9 1609.70  4359.5 1609.07  4365.3 1609.22  4374.4 1609.05
  4424.0 1607.78  4432.3 1607.84  4467.1 1606.93  4600.0 1604.89  4637.1 1604.84
  4642.9 1604.55  4674.3 1604.64  4680.1 1604.32  4695.8 1604.40  4723.1 1603.96
  4754.4 1603.83  4760.2 1603.57  4818.9 1603.05  5029.0 1601.71  5029.2 1601.21
  5032.7 1601.21  5033.0 1601.71  5061.1 1602.33  5121.4 1602.98  5272.2 1603.23
  5282.2 1603.08  5292.3 1603.30  5351.6 1603.20  5382.7 1603.51  5435.8 1603.38
#Mann=3,-1,0
  4324.6    0.05       0  5029.0   0.035       0  5033.0    0.05       0
Bank Sta=5029,5033
Exp/Cntr=0.3,0.1

Type RM Length L Ch R = 1,2864,229,229,229
BEGIN DESCRIPTION:
Mapping XS f1e829c8
END DESCRIPTION:
XS GIS Cut Line= 3
      1597503.26      6908372.38      1596888.67      6908114.56
      1595883.25      6907962.73
#Sta/Elev= 30
  4325.0 1609.15  4355.6 1608.24  4485.8 1605.82  4503.2 1605.73  4508.6 1605.46
  4594.2 1604.08  4609.1 1604.10  4632.9 1603.59  4709.6 1602.73  4715.0 1602.49
  4724.4 1602.61  4800.3 1601.92  4939.8 1601.47  5013.4 1600.71  5013.7 1600.21
  5017.2 1600.21  5017.4 1600.71  5070.0 1600.95  5202.7 1602.24  5207.7 1602.08
  5389.6 1602.49  5468.1 1602.29  5537.0 1602.74  5612.1 1602.84  5703.1 1602.58
  5871.3 1603.82  5876.3 1604.06  5925.6 1604.26  5956.0 1604.85  6008.3 1605.08
#Mann=3,-1,0
  4325.0    0.05       0  5013.4   0.035       0  5017.4    0.05       0
Bank Sta=5013.4,5017.4
Exp/Cntr=0.3,0.1

Type RM Length L Ch R = 1,2635,317,317,317
BEGIN DESCRIPTION:
Mapping XS 74685196
END DESCRIPTION:
XS GIS Cut Line= 3
      1597539.32      6908277.93      1596878.08      6907915.46
      1596178.66      6907590.97
#Sta/Elev= 30
  4246.0 1608.41  4256.4 1608.44  4316.2 1607.06  4375.9 1606.12  4387.8 1605.68
  4397.7 1605.69  4572.1 1602.61  4588.2 1602.61  4691.6 1601.37  4729.5 1601.40
  4786.9 1600.86  4854.6 1600.83  4898.2 1600.34  5005.4 1599.97  5005.7 1599.47
  5009.2 1599.47  5009.4 1599.97  5212.9 1600.74  5264.9 1601.26  5301.1 1601.27
  5407.8 1602.10  5413.4 1601.94  5436.3 1602.33  5505.0 1602.87  5653.9 1605.17
  5693.7 1605.32  5722.1 1605.72  5739.5 1605.64  5745.0 1605.89  5771.1 1606.10
#Mann=3,-1,0
  4246.0    0.05       0  5005.4   0.035       0  5009.4    0.05       0
Bank Sta=5005.4,5009.4
Exp/Cntr=0.3,0.1

Type RM Length L Ch R = 1,2318,426,426,426
BEGIN DESCRIPTION:
Deadman 13 2.0
END DESCRIPTION:
XS GIS Cut Line= 3
      1598155.02      6908238.01      1597038.48      6907653.87
      1596449.10      6907307.18
#Sta/Elev= 30
  3740.5 1616.62  3842.7 1615.47  4079.8 1611.87  4096.2 1611.39  4118.3 1611.25
  4192.0 1609.79  4245.1 1608.35  4294.9 1607.53  4339.0 1606.30  4406.4 1604.89
  4631.1 1601.10  4725.0 1600.10  4829.8 1599.69  4835.4 1599.38  4956.5 1599.31
  5004.2 1598.96  5004.5 1598.46  5008.3 1598.46  5008.6 1598.96  5059.2 1599.71
  5176.4 1600.74  5197.8 1600.66  5234.9 1601.14  5262.2 1601.73  5336.5 1602.64
  5342.3 1602.97  5432.2 1604.65  5570.8 1606.43  5619.5 1606.64  5684.4 1606.48
#Mann=3,-1,0
  3740.5    0.05       0  5004.2   0.035       0  5008.6    0.05       0
Bank Sta=5004.2,5008.6
Exp/Cntr=0.3,0.1

Type RM Length L Ch R = 1,1892,786,786,786
BEGIN DESCRIPTION:
Mapping XS 199d4625
END DESCRIPTION:
XS GIS Cut Line= 4
      1597908.38      6907900.08      1597396.53      6907456.33
      1597250.97      6907324.21      1596752.94      6907332.52
#Sta/Elev= 30
  4316.5 1611.25  4391.1 1610.13  4419.6 1609.28  4497.4 1607.68  4505.1 1607.24
  4511.7 1607.18  4540.2 1605.27  4575.3 1603.71  4632.3 1602.32  4638.9 1601.92
  4689.3 1600.87  4724.4 1599.81  4788.0 1598.95  4830.8 1598.74  4837.4 1598.48
  4859.3 1598.57  4865.9 1598.33  4986.5 1598.01  4998.6 1597.78  4998.9 1597.28
  5002.7 1597.28  5003.0 1597.78  5071.8 1598.15  5149.5 1597.78  5184.4 1598.30
  5296.5 1598.66  5516.5 1601.46  5586.5 1602.66  5636.5 1603.80  5688.6 1604.44
#Mann=3,-1,0
  4316.5    0.05       0  4998.6   0.035       0  5003.0    0.05       0
Bank Sta=4998.6,5003
Exp/Cntr=0.3,0.1

Type RM Length L Ch R = 1,1106,188,188,188
BEGIN DESCRIPTION:
Mapping XS de67416f
END DESCRIPTION:
XS GIS Cut Line= 3
      1598156.62      6907616.71      1598120.00      6907263.39
      1596862.39      6907297.95
#Sta/Elev= 30
  4670.0 1606.92  4719.0 1604.72  4734.1 1603.73  4739.2 1603.77  4769.2 1602.55
  4779.3 1602.41  4809.5 1600.83  4819.5 1600.64  4827.9 1600.16  4832.9 1600.23
  4889.9 1598.31  4950.2 1596.78  4990.4 1596.19  5088.0 1595.99  5088.3 1595.49
  5092.1 1595.49  5092.4 1595.99  5110.2 1596.20  5160.3 1596.11  5260.3 1596.43
  5370.1 1597.05  5375.1 1596.80  5430.4 1597.24  5520.4 1597.52  5670.5 1598.73
  5950.6 1598.61  6099.3 1600.07  6104.3 1599.95  6240.7 1601.88  6283.3 1602.72
#Mann=3,-1,0
  4670.0    0.05       0  5088.0   0.035       0  5092.4    0.05       0
Bank Sta=5088,5092.4
Exp/Cntr=0.3,0.1

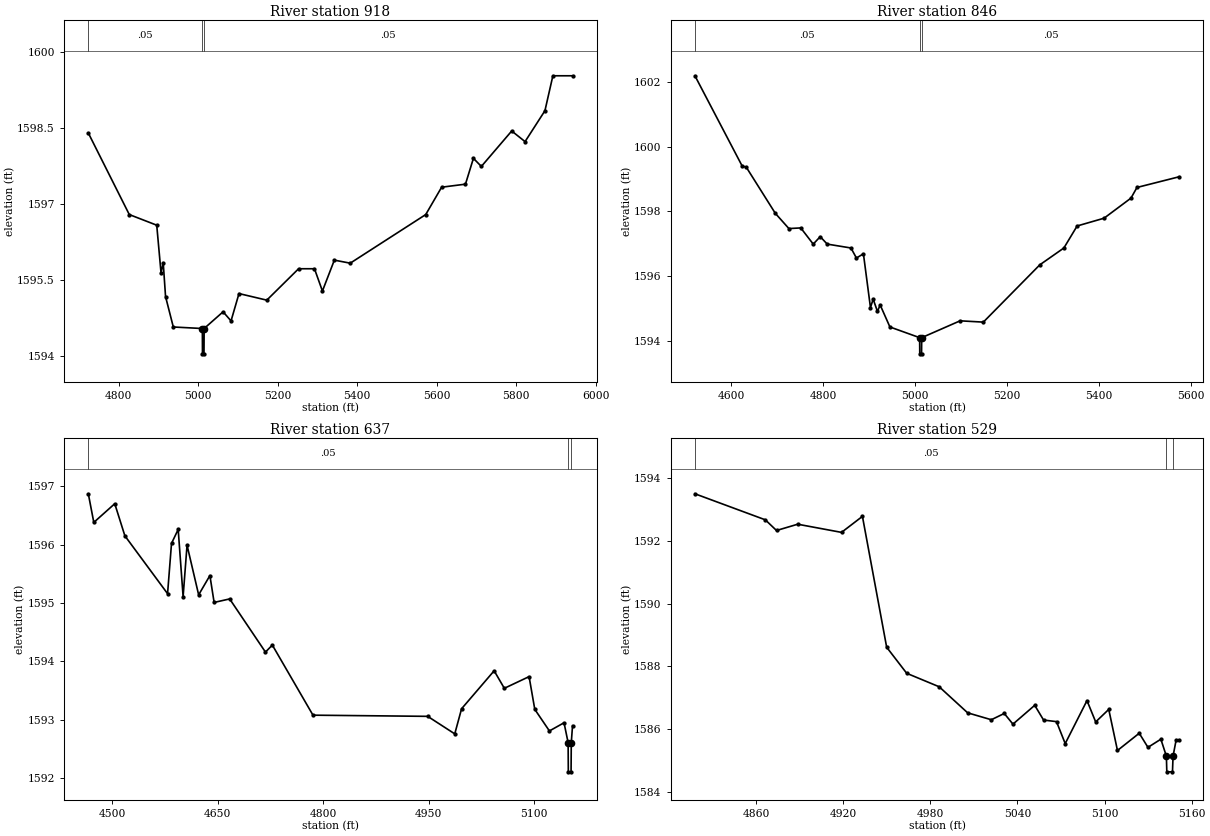
Type RM Length L Ch R = 1,918,72,72,72
BEGIN DESCRIPTION:
Mapping XS 6b8ace46
END DESCRIPTION:
XS GIS Cut Line= 4
      1598361.93      6907403.54      1598365.77      6907297.95
      1598317.77      6907198.11      1597315.52      6907203.87
#Sta/Elev= 30
  4723.3 1598.40  4826.4 1596.79  4895.5 1596.58  4906.3 1595.64  4911.8 1595.84
  4917.7 1595.17  4937.2 1594.57  5010.3 1594.54  5010.6 1594.04  5014.4 1594.04
  5014.8 1594.54  5062.5 1594.87  5082.5 1594.69  5102.5 1595.23  5172.5 1595.10
  5252.5 1595.72  5292.5 1595.72  5312.5 1595.28  5342.5 1595.89  5382.5 1595.83
  5572.5 1596.79  5612.5 1597.33  5672.5 1597.39  5692.5 1597.90  5712.5 1597.74
  5788.9 1598.44  5822.5 1598.23  5872.5 1598.84  5892.5 1599.53  5942.0 1599.53
#Mann=3,-1,0
  4723.3    0.05       0  5010.3    0.03       0  5014.8    0.05       0
Bank Sta=5010.3,5014.8
Exp/Cntr=0.3,0.1

Type RM Length L Ch R = 1,846,209,209,209
BEGIN DESCRIPTION:
Mapping XS 6413d2d1
END DESCRIPTION:
XS GIS Cut Line= 4
      1598363.13      6907561.74      1598442.20      6907366.26
      1598182.98      6906959.86      1597875.43      6906773.13
#Sta/Elev= 30
  4521.7 1602.19  4624.1 1599.41  4633.6 1599.36  4696.5 1597.94  4726.0 1597.47
  4751.8 1597.49  4778.9 1596.99  4794.1 1597.22  4809.3 1596.99  4860.9 1596.87
  4872.8 1596.56  4888.0 1596.69  4903.3 1595.03  4909.2 1595.29  4918.5 1594.91
  4924.4 1595.11  4945.6 1594.43  5010.2 1594.10  5010.5 1593.60  5014.4 1593.60
  5014.7 1594.10  5098.2 1594.62  5148.7 1594.58  5271.5 1596.35  5323.8 1596.87
  5352.6 1597.55  5411.1 1597.79  5469.6 1598.41  5482.7 1598.74  5574.4 1599.07
#Mann=3,-1,0
  4521.7    0.05       0  5010.2    0.05       0  5014.7    0.05       0
Bank Sta=5010.2,5014.7
Exp/Cntr=0.3,0.1

Type RM Length L Ch R = 1,637,108,108,108
BEGIN DESCRIPTION:
Mapping XS e1a3aff9
END DESCRIPTION:
XS GIS Cut Line= 3
      1598682.91      6907481.34      1598436.25      6907008.27
      1598339.98      6906886.67
#Sta/Elev= 30
  4466.0 1596.87  4473.8 1596.38  4503.6 1596.70  4518.0 1596.15  4578.7 1595.16
  4584.3 1596.02  4593.8 1596.26  4600.8 1595.11  4606.4 1595.99  4622.9 1595.14
  4638.9 1595.47  4644.9 1595.01  4667.0 1595.07  4717.9 1594.16  4727.7 1594.28
  4785.5 1593.08  4948.6 1593.06  4987.1 1592.76  4996.8 1593.19  5043.1 1593.84
  5057.6 1593.54  5092.8 1593.74  5100.9 1593.18  5121.7 1592.81  5142.5 1592.95
  5148.3 1592.61  5148.6 1592.11  5152.5 1592.11  5152.8 1592.61  5154.6 1592.90
#Mann=3,-1,0
  4466.0    0.05       0  5148.3    0.05       0  5152.8    0.05       0
Bank Sta=5148.3,5152.8
Exp/Cntr=0.3,0.1

Type RM Length L Ch R = 1,529,0,0,0
BEGIN DESCRIPTION:
Deadman 13 1.0
END DESCRIPTION:
XS GIS Cut Line= 3
      1598590.94      6907108.20      1598505.00      6906938.00
      1598386.55      6906858.00
#Sta/Elev= 30
  4817.8 1593.50  4866.3 1592.67  4874.0 1592.33  4888.6 1592.53  4918.8 1592.27
  4933.2 1592.78  4949.9 1588.61  4963.7 1587.78  4986.1 1587.35  5005.7 1586.52
  5022.0 1586.30  5030.9 1586.50  5036.9 1586.16  5051.9 1586.76  5058.0 1586.29
  5066.9 1586.24  5072.9 1585.54  5087.9 1586.91  5093.9 1586.23  5102.9 1586.63
  5108.9 1585.32  5123.9 1585.87  5129.9 1585.42  5138.8 1585.68  5142.6 1585.14
  5142.9 1584.64  5146.8 1584.64  5147.2 1585.14  5149.3 1585.65  5151.4 1585.65
#Mann=3,-1,0
  4817.8    0.05       0  5142.6    0.05       0  5147.2    0.05       0
Bank Sta=5142.6,5147.2
Exp/Cntr=0.3,0.1

Chan Stop Cuts=-1