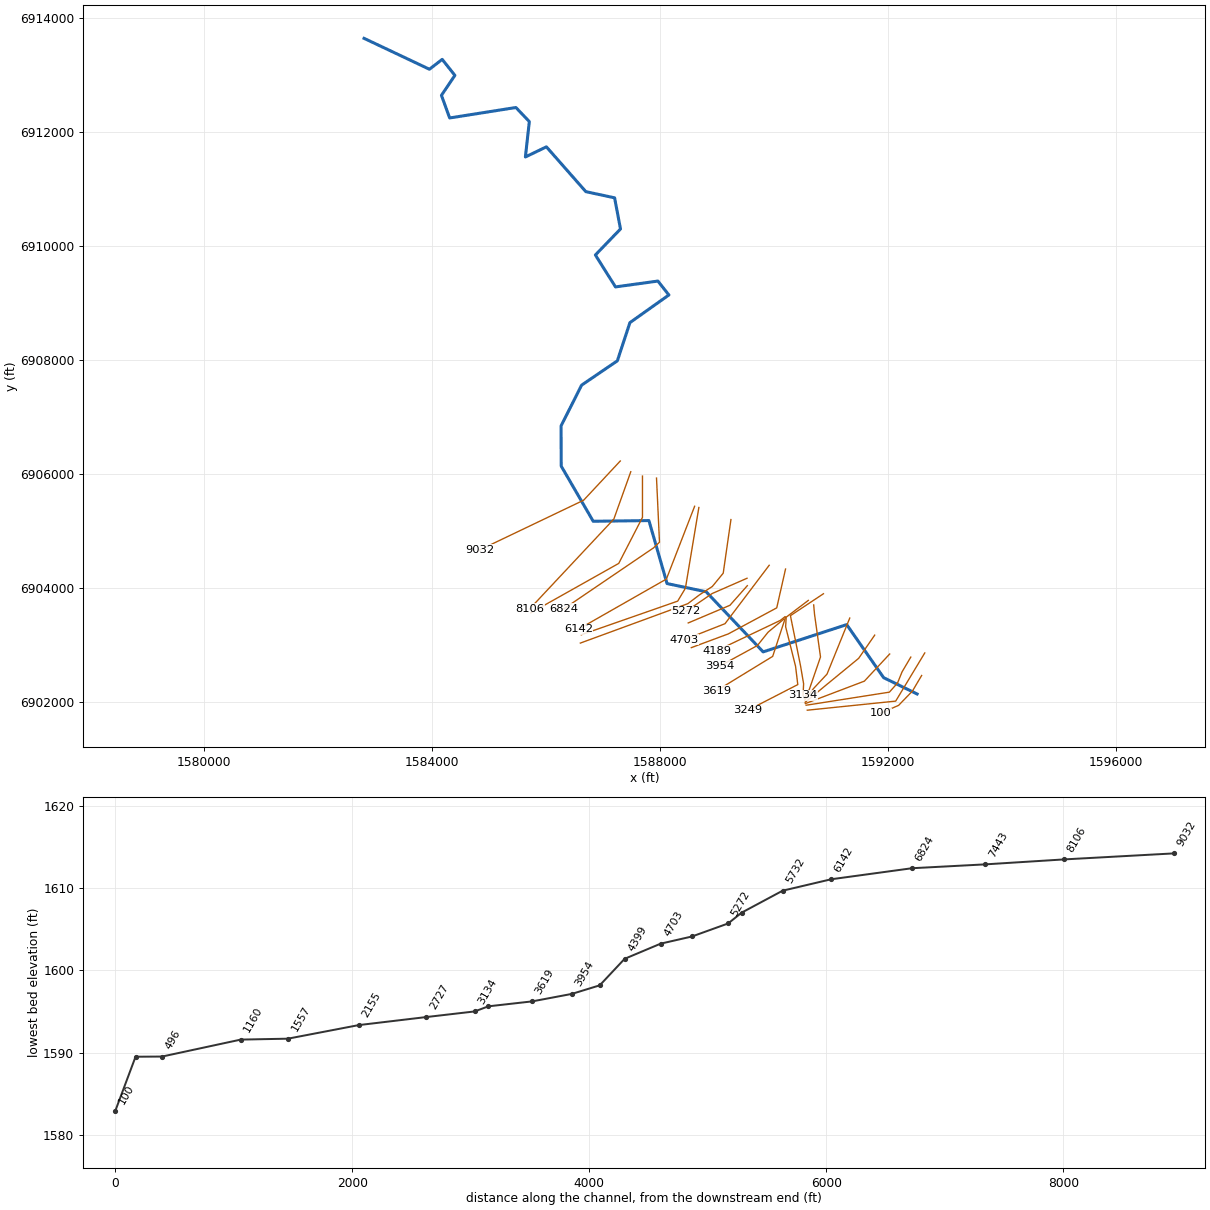
--- Deadman 15.prj (project) ---

Proj Title=Deadman 15 Base Level Engineering
Current Plan=p01
Default Exp/Contr=0.3,0.1
English Units
Geom File=g01
Flow File=f01
Plan File=p01
Y Axis Title=Elevation
X Axis Title(PF)=Main Channel Distance
X Axis Title(XS)=Station
BEGIN DESCRIPTION:
Deadman 15
END DESCRIPTION:
DSS Export Rating Curves= 0
DSS Export Rating Curve Sorted= 0
DSS Export Volume Flow Curves= 0
DXF OffsetX= 0
DXF OffsetY= 0
DXF ScaleX= 1
DXF ScaleY= 10

--- Deadman 15.p01 (plan) ---

Plan Title=Multiple Run
Short Identifier=Multiple
Geom File=g01
Flow File=f01
Subcritical Flow
K Sum by GR= 0
Std Step Tol= 0.01
Critical Tol= 0.01
Num of Std Step Trials= 20
Max Error Tol= 0.3
Flow Tol Ratio= 0.001
Split Flow NTrial= 30
Split Flow Tol= 0.02
Split Flow Ratio= 0.02
Log Output Level= 0
Friction Slope Method= 1
Unsteady Friction Slope Method= 2
Unsteady Bridges Friction Slope Method= 1
Parabolic Critical Depth
Global Vel Dist=  1 , 1 , 1
Global Log Level= 0
CheckData=True
Encroach Param= -1, 0, 0, 0
BEGIN DESCRIPTION:
Multiple Run
END DESCRIPTION:

--- Deadman 15.f01 (steady flow) ---

Flow Title=Multiple
Number of Profiles=7
Profile Names=10-year,25-year,50-year,1pct_min,100-year,1pct_plu,500-year
River Rch & RM= Deadman 15,Reach-1,9032
     133     175     207     123     244     488     344
River Rch & RM= Deadman 15,Reach-1,8106
     228     310     376     227     452     902     663
River Rch & RM= Deadman 15,Reach-1,6142
     291     399     487     295     588    1174     872
Boundary for River Rch & Prof#=Deadman 15,Reach-1,1
Up Type=0
Dn Type=3
Dn Slope=0.009
Boundary for River Rch & Prof#=Deadman 15,Reach-1,2
Up Type=0
Dn Type=3
Dn Slope=0.009
Boundary for River Rch & Prof#=Deadman 15,Reach-1,3
Up Type=0
Dn Type=3
Dn Slope=0.009
Boundary for River Rch & Prof#=Deadman 15,Reach-1,4
Up Type=0
Dn Type=3
Dn Slope=0.009
Boundary for River Rch & Prof#=Deadman 15,Reach-1,5
Up Type=0
Dn Type=3
Dn Slope=0.009
Boundary for River Rch & Prof#=Deadman 15,Reach-1,6
Up Type=0
Dn Type=3
Dn Slope=0.009
Boundary for River Rch & Prof#=Deadman 15,Reach-1,7
Up Type=0
Dn Type=3
Dn Slope=0.009

--- Deadman 15.g01 (geometry) ---

Geom Title=Existing Conditions

River Reach=Deadman 15,Reach-1
Reach XY= 30
      1582805.00      6913638.00      1583951.67      6913095.59
      1584175.39      6913268.95      1584398.00      6912988.22
      1584162.20      6912638.30      1584306.25      6912241.36
      1585468.30      6912424.66      1585703.97      6912177.56
      1585634.48      6911557.08      1586003.37      6911734.88
      1586695.00      6910948.63      1587199.27      6910840.55
      1587302.87      6910293.94      1586862.07      6909837.99
      1587215.07      6909278.00      1587958.58      6909380.50
      1588151.54      6909136.50      1587468.23      6908651.67
      1587247.66      6907981.67      1586621.11      6907555.16
      1586260.46      6906840.45      1586263.05      6906134.66
      1586824.26      6905167.31      1587801.50      6905179.54
      1588119.35      6904074.66      1588804.91      6903930.83
      1589804.71      6902876.57      1591270.34      6903354.82
      1591918.24      6902424.24      1592505.00      6902138.00

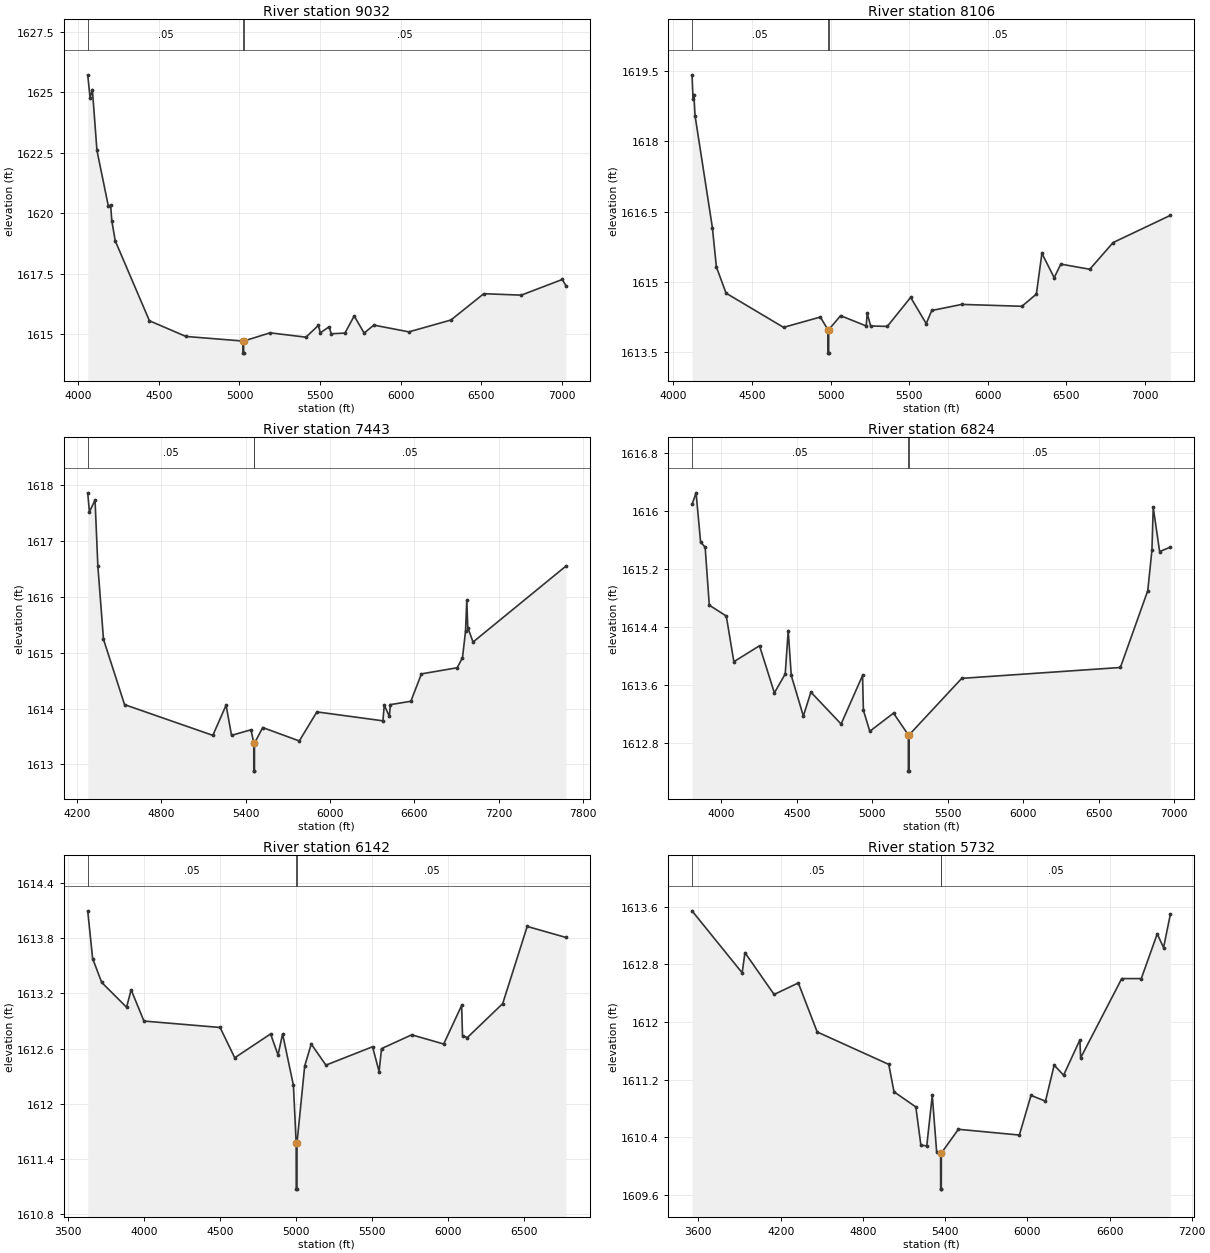
Type RM Length L Ch R = 1,9032,926,926,926
BEGIN DESCRIPTION:
Deadman 15 27.0
END DESCRIPTION:
XS GIS Cut Line= 3
      1587299.16      6906224.87      1586656.66      6905536.95
      1584829.97      6904662.98
#Sta/Elev= 30
  4058.7 1625.73  4073.5 1624.78  4087.7 1625.12  4116.0 1622.60  4186.9 1620.29
  4201.0 1620.34  4207.9 1619.70  4229.4 1618.86  4441.4 1615.55  4668.1 1614.90
  5022.0 1614.71  5022.3 1614.21  5025.8 1614.21  5026.0 1614.71  5189.6 1615.05
  5412.0 1614.87  5489.6 1615.36  5501.0 1615.05  5556.1 1615.30  5569.0 1615.01
  5654.1 1615.04  5711.3 1615.75  5773.0 1615.04  5833.3 1615.37  6050.6 1615.09
  6311.1 1615.58  6515.1 1616.67  6747.4 1616.61  7002.3 1617.26  7025.0 1616.99
#Mann=3,-1,0
  4058.7    0.05       0  5022.0   0.035       0  5026.0    0.05       0
Bank Sta=5022,5026
Exp/Cntr=0.3,0.1

Type RM Length L Ch R = 1,8106,663,663,663
BEGIN DESCRIPTION:
Mapping XS 205f11a6
END DESCRIPTION:
XS GIS Cut Line= 3
      1587483.25      6906036.06      1587185.87      6905205.29
      1585709.20      6903629.55
#Sta/Elev= 30
  4118.9 1619.42  4125.3 1618.91  4130.6 1619.00  4138.1 1618.55  4248.4 1616.16
  4273.9 1615.32  4335.4 1614.76  4701.0 1614.03  4934.8 1614.25  4983.3 1613.98
  4983.7 1613.48  4987.9 1613.48  4988.2 1613.98  5063.8 1614.28  5226.5 1614.06
  5233.3 1614.33  5254.8 1614.06  5360.8 1614.05  5509.3 1614.67  5608.4 1614.11
  5643.6 1614.39  5834.6 1614.52  6217.1 1614.48  6308.9 1614.74  6344.1 1615.61
  6422.2 1615.09  6464.3 1615.38  6648.4 1615.27  6796.9 1615.84  7160.8 1616.42
#Mann=3,-1,0
  4118.9    0.05       0  4983.3    0.03       0  4988.2    0.05       0
Bank Sta=4983.3,4988.2
Exp/Cntr=0.3,0.1

Type RM Length L Ch R = 1,7443,619,619,619
BEGIN DESCRIPTION:
Mapping XS 98bcc42b
END DESCRIPTION:
XS GIS Cut Line= 4
      1587688.28      6905960.21      1587688.28      6905236.26
      1587272.09      6904428.37      1585729.86      6903561.09
#Sta/Elev= 30
  4276.8 1617.86  4289.0 1617.52  4329.0 1617.73  4349.0 1616.55  4389.0 1615.24
  4539.0 1614.07  5166.8 1613.52  5261.1 1614.06  5299.8 1613.52  5438.4 1613.62
  5458.0 1613.38  5458.4 1612.88  5462.7 1612.88  5463.1 1613.38  5521.5 1613.66
  5781.8 1613.42  5906.9 1613.94  6376.6 1613.78  6386.0 1614.06  6422.5 1613.86
  6429.4 1614.07  6575.3 1614.13  6650.6 1614.62  6904.9 1614.73  6942.5 1614.91
  6964.2 1615.38  6973.2 1615.94  6980.1 1615.45  7017.7 1615.19  7678.9 1616.55
#Mann=3,-1,0
  4276.8    0.05       0  5458.0   0.035       0  5463.1    0.05       0
Bank Sta=5458,5463.1
Exp/Cntr=0.3,0.1

Type RM Length L Ch R = 1,6824,682,682,682
BEGIN DESCRIPTION:
Mapping XS d48238cf
END DESCRIPTION:
XS GIS Cut Line= 4
      1587934.59      6905924.86      1587986.68      6904800.70
      1587882.51      6904700.88      1586311.31      6903633.16
#Sta/Elev= 30
  3806.3 1616.09  3833.2 1616.25  3863.2 1615.57  3893.3 1615.50  3920.7 1614.70
  4033.4 1614.55  4083.5 1613.92  4253.6 1614.14  4352.0 1613.49  4423.8 1613.75
  4443.8 1614.35  4463.9 1613.73  4544.0 1613.17  4594.0 1613.50  4794.2 1613.06
  4936.3 1613.73  4941.9 1613.25  4984.3 1612.96  5141.4 1613.21  5239.6 1612.91
  5240.0 1612.41  5244.4 1612.41  5244.8 1612.91  5593.5 1613.69  6644.7 1613.84
  6826.1 1614.90  6853.8 1615.46  6862.3 1616.05  6904.7 1615.44  6975.6 1615.50
#Mann=3,-1,0
  3806.3    0.05       0  5239.6   0.035       0  5244.8    0.05       0
Bank Sta=5239.6,5244.8
Exp/Cntr=0.3,0.1

Type RM Length L Ch R = 1,6142,410,410,410
BEGIN DESCRIPTION:
Mapping XS ffb49217
END DESCRIPTION:
XS GIS Cut Line= 3
      1588603.00      6905430.04      1588108.21      6904154.00
      1586563.16      6903272.98
#Sta/Elev= 30
  3628.1 1614.10  3660.6 1613.58  3720.4 1613.32  3883.8 1613.05  3913.8 1613.24
  3998.1 1612.90  4499.1 1612.83  4595.6 1612.50  4831.5 1612.76  4880.5 1612.53
  4910.4 1612.76  4981.7 1612.20  4999.8 1611.57  5000.2 1611.07  5004.7 1611.07
  5005.1 1611.57  5055.8 1612.41  5099.0 1612.65  5195.5 1612.42  5502.3 1612.62
  5545.5 1612.35  5561.4 1612.60  5760.1 1612.75  5970.4 1612.65  6088.6 1613.07
  6094.3 1612.74  6126.0 1612.72  6358.8 1613.09  6519.9 1613.93  6775.3 1613.81
#Mann=3,-1,0
  3628.1    0.05       0  4999.8   0.035       0  5005.1    0.05       0
Bank Sta=4999.8,5005.1
Exp/Cntr=0.3,0.1

Type RM Length L Ch R = 1,5732,345,345,345
BEGIN DESCRIPTION:
Mapping XS 044126f0
END DESCRIPTION:
XS GIS Cut Line= 4
      1588677.37      6905408.96      1588441.26      6903992.26
      1588305.84      6903766.57      1586614.85      6903176.28
#Sta/Elev= 30
  3553.3 1613.54  3919.2 1612.68  3939.5 1612.96  4152.4 1612.38  4329.0 1612.54
  4466.7 1611.86  4989.2 1611.41  5027.3 1611.03  5186.6 1610.82  5223.6 1610.29
  5266.5 1610.28  5306.6 1610.98  5338.4 1610.20  5367.5 1610.18  5367.9 1609.68
  5372.4 1609.68  5372.8 1610.18  5497.2 1610.51  5942.1 1610.43  6027.1 1610.98
  6132.8 1610.90  6196.3 1611.40  6265.0 1611.26  6383.9 1611.75  6389.2 1611.50
  6689.2 1612.60  6831.8 1612.60  6948.3 1613.22  6994.5 1613.03  7043.8 1613.49
#Mann=3,-1,0
  3553.3    0.05       0  5367.5   0.035       0  5372.8    0.05       0
Bank Sta=5367.5,5372.8
Exp/Cntr=0.3,0.1

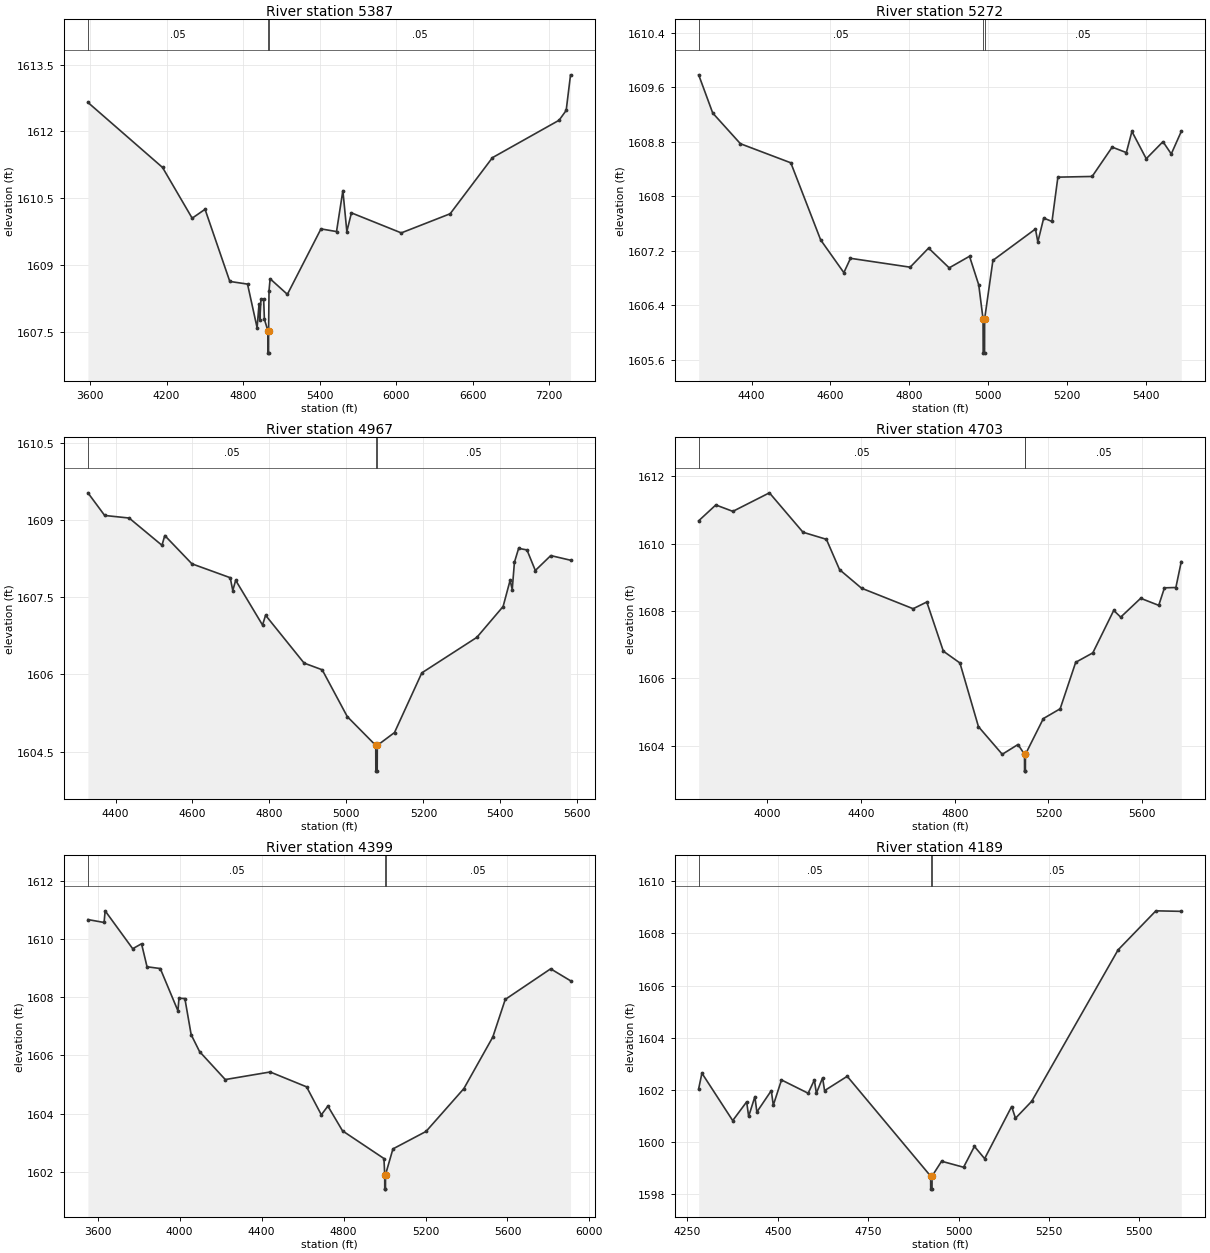
Type RM Length L Ch R = 1,5387,115,115,115
BEGIN DESCRIPTION:
Mapping XS 68ef7c21
END DESCRIPTION:
XS GIS Cut Line= 6
      1589239.87      6905197.16      1589104.45      6904256.15
      1588913.48      6904023.51      1588694.73      6903881.15
      1588482.92      6903721.43      1586598.73      6903030.90
#Sta/Elev= 30
  3583.2 1612.65  4168.3 1611.19  4400.7 1610.05  4501.7 1610.25  4695.9 1608.63
  4834.9 1608.57  4909.9 1607.59  4925.0 1608.12  4931.0 1607.76  4940.2 1608.23
  4961.3 1608.23  4967.2 1607.78  4994.8 1607.52  4995.2 1607.02  4999.7 1607.02
  5000.1 1607.52  5003.4 1608.42  5012.0 1608.69  5147.3 1608.34  5410.8 1609.81
  5532.8 1609.75  5582.6 1610.67  5613.7 1609.75  5649.5 1610.17  6040.6 1609.72
  6424.0 1610.15  6755.5 1611.41  7278.0 1612.25  7333.7 1612.47  7367.9 1613.27
#Mann=3,-1,0
  3583.2    0.05       0  4994.8   0.035       0  5000.1    0.05       0
Bank Sta=4994.8,5000.1
Exp/Cntr=0.3,0.1

Type RM Length L Ch R = 1,5272,305,305,305
BEGIN DESCRIPTION:
Mapping XS 188af738
END DESCRIPTION:
XS GIS Cut Line= 3
      1589521.96      6904167.60      1588910.01      6903899.38
      1588451.66      6903586.87
#Sta/Elev= 30
  4266.1 1609.78  4301.7 1609.22  4371.9 1608.77  4499.6 1608.49  4575.2 1607.36
  4634.0 1606.88  4650.8 1607.09  4802.0 1606.96  4848.7 1607.24  4900.9 1606.95
  4952.4 1607.12  4975.8 1606.70  4986.7 1606.20  4987.0 1605.70  4990.5 1605.70
  4990.7 1606.20  5011.7 1607.06  5119.5 1607.52  5125.5 1607.33  5140.4 1607.68
  5161.4 1607.63  5176.3 1608.28  5263.1 1608.29  5313.9 1608.72  5349.8 1608.64
  5363.9 1608.95  5400.2 1608.55  5442.6 1608.80  5463.6 1608.62  5489.0 1608.95
#Mann=3,-1,0
  4266.1    0.05       0  4986.7   0.035       0  4990.7    0.05       0
Bank Sta=4986.7,4990.7
Exp/Cntr=0.3,0.1

Type RM Length L Ch R = 1,4967,264,264,264
BEGIN DESCRIPTION:
Mapping XS a664d839
END DESCRIPTION:
XS GIS Cut Line= 3
      1589527.21      6904037.41      1589222.51      6903693.65
      1588490.78      6903383.77
#Sta/Elev= 30
  4328.3 1609.53  4371.8 1609.09  4435.4 1609.04  4520.7 1608.51  4528.0 1608.70
  4598.5 1608.15  4698.0 1607.88  4704.7 1607.63  4712.2 1607.83  4782.0 1606.96
  4789.9 1607.15  4890.0 1606.22  4937.0 1606.09  5002.2 1605.18  5076.2 1604.62
  5076.4 1604.12  5079.9 1604.12  5080.2 1604.62  5124.9 1604.87  5195.9 1606.03
  5338.8 1606.72  5407.1 1607.32  5425.3 1607.83  5430.8 1607.65  5436.5 1608.18
  5447.4 1608.45  5469.1 1608.42  5490.8 1608.02  5530.9 1608.31  5582.3 1608.22
#Mann=3,-1,0
  4328.3    0.05       0  5076.2   0.035       0  5080.2    0.05       0
Bank Sta=5076.2,5080.2
Exp/Cntr=0.3,0.1

Type RM Length L Ch R = 1,4703,304,304,304
BEGIN DESCRIPTION:
Mapping XS c005ea17
END DESCRIPTION:
XS GIS Cut Line= 3
      1589911.03      6904395.52      1589136.08      6903371.02
      1588413.70      6903086.44
#Sta/Elev= 30
  3706.2 1610.68  3779.4 1611.15  3852.2 1610.96  4008.3 1611.51  4151.8 1610.34
  4251.7 1610.13  4307.9 1609.23  4401.6 1608.68  4622.1 1608.07  4680.4 1608.27
  4751.1 1606.81  4821.9 1606.46  4901.0 1604.57  5002.7 1603.75  5069.9 1604.04
  5097.7 1603.75  5097.9 1603.25  5101.4 1603.25  5101.7 1603.75  5178.2 1604.81
  5249.9 1605.10  5316.3 1606.48  5389.4 1606.76  5478.7 1608.02  5508.5 1607.82
  5593.8 1608.38  5670.9 1608.17  5695.3 1608.69  5744.1 1608.70  5767.2 1609.47
#Mann=3,-1,0
  3706.2    0.05       0  5097.7   0.035       0  5101.7    0.05       0
Bank Sta=5097.7,5101.7
Exp/Cntr=0.3,0.1

Type RM Length L Ch R = 1,4399,210,210,210
BEGIN DESCRIPTION:
Mapping XS 7138fe08
END DESCRIPTION:
XS GIS Cut Line= 4
      1590197.60      6904329.25      1590043.16      6903648.38
      1589193.00      6903191.52      1588545.01      6902950.71
#Sta/Elev= 30
  3553.0 1610.66  3631.9 1610.56  3637.0 1610.96  3771.5 1609.66  3814.6 1609.83
  3841.4 1609.04  3905.9 1608.98  3992.1 1607.53  3997.3 1607.96  4026.0 1607.95
  4056.7 1606.71  4097.7 1606.13  4223.1 1605.17  4442.1 1605.43  4619.8 1604.92
  4691.8 1603.96  4723.7 1604.26  4795.2 1603.41  4997.3 1602.46  5001.0 1601.91
  5001.2 1601.41  5004.7 1601.41  5005.0 1601.91  5041.1 1602.79  5202.7 1603.39
  5387.2 1604.86  5528.4 1606.63  5589.1 1607.92  5810.6 1608.97  5907.6 1608.56
#Mann=3,-1,0
  3553.0    0.05       0  5001.0    0.03       0  5005.0    0.05       0
Bank Sta=5001,5005
Exp/Cntr=0.3,0.1

Type RM Length L Ch R = 1,4189,235,235,235
BEGIN DESCRIPTION:
Mapping XS 9acc3a1a
END DESCRIPTION:
XS GIS Cut Line= 3
      1590184.97      6903490.14      1590104.82      6903428.09
      1588991.57      6902898.17
#Sta/Elev= 30
  4281.5 1602.04  4290.5 1602.64  4375.6 1600.82  4414.2 1601.54  4419.7 1600.98
  4436.9 1601.74  4442.4 1601.15  4482.3 1601.97  4487.8 1601.41  4510.5 1602.38
  4584.2 1601.87  4601.4 1602.38  4606.9 1601.87  4624.1 1602.46  4629.6 1601.97
  4692.2 1602.52  4922.8 1598.69  4923.1 1598.19  4926.6 1598.19  4926.8 1598.69
  4953.1 1599.26  5013.9 1599.03  5043.9 1599.83  5072.1 1599.36  5146.8 1601.36
  5157.4 1600.91  5202.2 1601.56  5441.0 1607.37  5545.6 1608.87  5615.8 1608.85
#Mann=3,-1,0
  4281.5    0.05       0  4922.8    0.05       0  4926.8    0.05       0
Bank Sta=4922.8,4926.8
Exp/Cntr=0.3,0.1

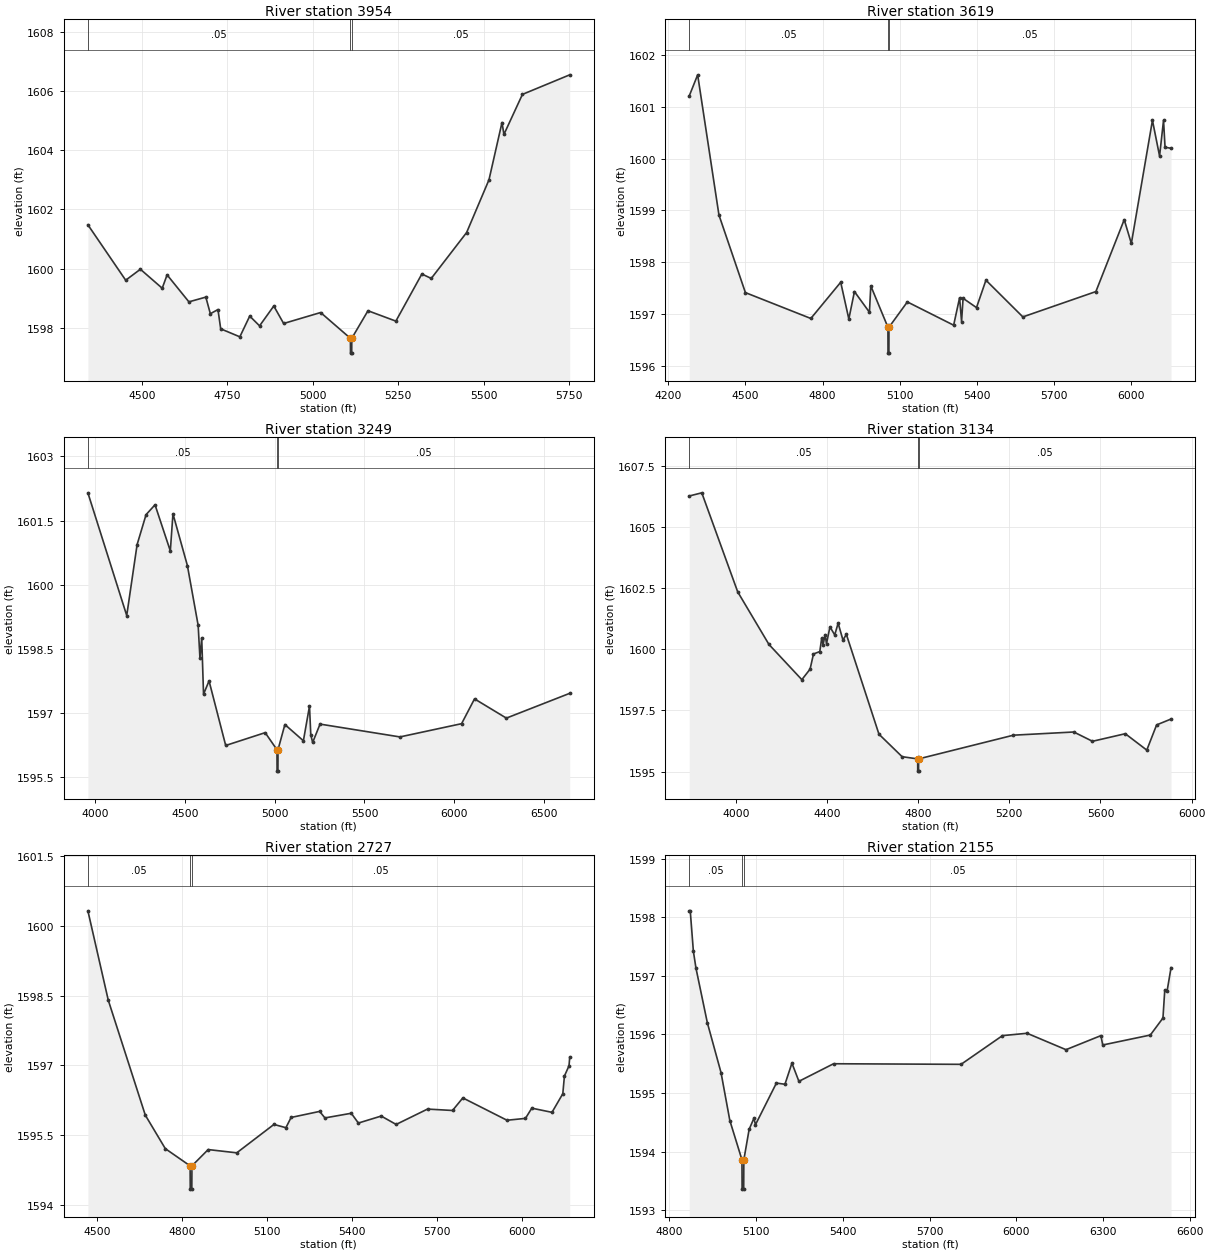
Type RM Length L Ch R = 1,3954,335,335,335
BEGIN DESCRIPTION:
Mapping XS e0d599b7
END DESCRIPTION:
XS GIS Cut Line= 4
      1590167.79      6903451.44      1589891.78      6903222.30
      1589704.28      6902987.92      1589045.40      6902628.53
#Sta/Elev= 30
  4342.1 1601.48  4452.7 1599.61  4495.7 1599.98  4559.5 1599.34  4573.8 1599.79
  4637.6 1598.88  4687.1 1599.04  4700.3 1598.48  4722.6 1598.62  4730.6 1597.97
  4786.6 1597.70  4815.5 1598.40  4844.3 1598.07  4885.9 1598.74  4914.7 1598.15
  5022.9 1598.52  5110.0 1597.65  5110.3 1597.15  5113.8 1597.15  5114.0 1597.65
  5161.4 1598.58  5243.0 1598.23  5319.0 1599.82  5346.5 1599.67  5450.0 1601.22
  5515.4 1603.00  5553.4 1604.93  5559.1 1604.53  5613.2 1605.88  5751.5 1606.54
#Mann=3,-1,0
  4342.1    0.05       0  5110.0    0.05       0  5114.0    0.05       0
Bank Sta=5110,5114
Exp/Cntr=0.3,0.1

Type RM Length L Ch R = 1,3619,370,370,370
BEGIN DESCRIPTION:
Deadman 15 1.35
END DESCRIPTION:
XS GIS Cut Line= 3
      1590199.07      6903487.92      1589972.51      6902797.82
      1588993.32      6902198.85
#Sta/Elev= 30
  4281.5 1601.21  4314.4 1601.62  4397.2 1598.91  4500.1 1597.41  4754.6 1596.91
  4870.8 1597.61  4902.4 1596.90  4924.2 1597.43  4982.6 1597.03  4987.8 1597.54
  5054.5 1596.74  5054.8 1596.24  5058.3 1596.24  5058.5 1596.74  5130.0 1597.23
  5310.1 1596.78  5333.2 1597.31  5340.9 1596.85  5346.8 1597.30  5399.0 1597.12
  5435.7 1597.65  5579.3 1596.94  5863.4 1597.43  5973.6 1598.82  6001.3 1598.36
  6083.4 1600.74  6111.1 1600.05  6126.5 1600.74  6132.4 1600.22  6155.7 1600.20
#Mann=3,-1,0
  4281.5    0.05       0  5054.5    0.05       0  5058.5    0.05       0
Bank Sta=5054.5,5058.5
Exp/Cntr=0.3,0.1

Type RM Length L Ch R = 1,3249,115,115,115
BEGIN DESCRIPTION:
Deadman 15 1.3
END DESCRIPTION:
XS GIS Cut Line= 6
      1590597.53      6903779.60      1590209.49      6903485.32
      1590199.07      6903318.65      1590373.55      6902623.34
      1590412.37      6902302.65      1589530.71      6901849.05
#Sta/Elev= 30
  3958.6 1602.15  4175.1 1599.28  4233.0 1600.94  4282.9 1601.64  4332.8 1601.87
  4418.1 1600.79  4432.7 1601.66  4513.1 1600.45  4573.2 1599.05  4583.2 1598.28
  4593.0 1598.76  4603.2 1597.44  4633.9 1597.75  4726.7 1596.24  4946.7 1596.54
  5012.5 1596.14  5013.0 1595.64  5017.8 1595.64  5018.2 1596.14  5056.6 1596.73
  5159.7 1596.35  5193.7 1597.16  5200.9 1596.49  5211.3 1596.31  5252.5 1596.74
  5697.8 1596.44  6041.4 1596.75  6113.5 1597.33  6290.9 1596.88  6644.0 1597.46
#Mann=3,-1,0
  3958.6    0.05       0  5012.5    0.05       0  5018.2    0.05       0
Bank Sta=5012.5,5018.2
Exp/Cntr=0.3,0.1

Type RM Length L Ch R = 1,3134,407,407,407
BEGIN DESCRIPTION:
Mapping XS f94612c7
END DESCRIPTION:
XS GIS Cut Line= 5
      1590862.27      6903896.06      1590283.49      6903511.45
      1590458.99      6902641.38      1590514.67      6902317.72
      1590505.06      6902114.78
#Sta/Elev= 30
  3795.4 1606.27  3850.6 1606.40  4008.2 1602.35  4145.3 1600.20  4289.6 1598.76
  4325.7 1599.19  4340.7 1599.81  4368.4 1599.91  4376.8 1600.46  4382.8 1600.19
  4391.8 1600.60  4397.8 1600.23  4412.9 1600.92  4433.9 1600.59  4448.9 1601.07
  4470.0 1600.38  4485.0 1600.61  4628.0 1596.53  4729.6 1595.61  4797.9 1595.52
  4798.1 1595.02  4801.6 1595.02  4801.9 1595.52  5218.1 1596.49  5482.8 1596.62
  5564.9 1596.24  5708.7 1596.55  5803.1 1595.88  5846.2 1596.91  5909.5 1597.15
#Mann=3,-1,0
  3795.4    0.05       0  4797.9    0.05       0  4801.9    0.05       0
Bank Sta=4797.9,4801.9
Exp/Cntr=0.3,0.1

Type RM Length L Ch R = 1,2727,572,572,572
BEGIN DESCRIPTION:
Deadman 15 1.15
END DESCRIPTION:
XS GIS Cut Line= 5
      1590691.26      6903699.73      1590706.15      6903536.67
      1590811.05      6902787.40      1590616.08      6902222.42
      1590529.16      6902060.24
#Sta/Elev= 30
  4466.1 1600.32  4538.1 1598.40  4668.9 1595.93  4739.6 1595.21  4827.2 1594.84
  4827.7 1594.34  4833.2 1594.34  4833.7 1594.84  4891.0 1595.19  4992.0 1595.12
  5123.3 1595.73  5165.6 1595.66  5183.9 1595.88  5284.8 1596.01  5303.4 1595.87
  5396.4 1595.97  5421.6 1595.76  5502.2 1595.91  5555.0 1595.73  5665.8 1596.06
  5754.1 1596.03  5790.6 1596.30  5946.6 1595.82  6011.8 1595.86  6034.1 1596.08
  6105.5 1595.99  6143.7 1596.39  6149.4 1596.77  6165.6 1596.99  6168.1 1597.17
#Mann=3,-1,0
  4466.1    0.05       0  4827.2    0.05       0  4833.7    0.05       0
Bank Sta=4827.2,4833.7
Exp/Cntr=0.3,0.1

Type RM Length L Ch R = 1,2155,598,598,598
BEGIN DESCRIPTION:
Deadman 15 1.1
END DESCRIPTION:
XS GIS Cut Line= 4
      1591324.08      6903469.72      1590925.07      6902486.36
      1590691.03      6902236.15      1590534.07      6902029.55
#Sta/Elev= 30
  4870.4 1598.11  4874.0 1598.11  4884.8 1597.42  4893.8 1597.13  4933.0 1596.20
  4980.2 1595.35  5010.7 1594.53  5052.5 1593.86  5053.0 1593.36  5058.5 1593.36
  5059.0 1593.86  5077.3 1594.38  5093.8 1594.57  5099.2 1594.46  5171.4 1595.17
  5200.9 1595.15  5225.0 1595.51  5249.1 1595.20  5368.7 1595.50  5808.9 1595.49
  5951.8 1595.98  6036.8 1596.02  6171.1 1595.74  6291.6 1595.98  6297.9 1595.82
  6462.2 1595.99  6505.8 1596.28  6512.1 1596.76  6520.4 1596.75  6533.7 1597.14
#Mann=3,-1,0
  4870.4    0.05       0  5052.5   0.035       0  5059.0    0.05       0
Bank Sta=5052.5,5059
Exp/Cntr=0.3,0.1

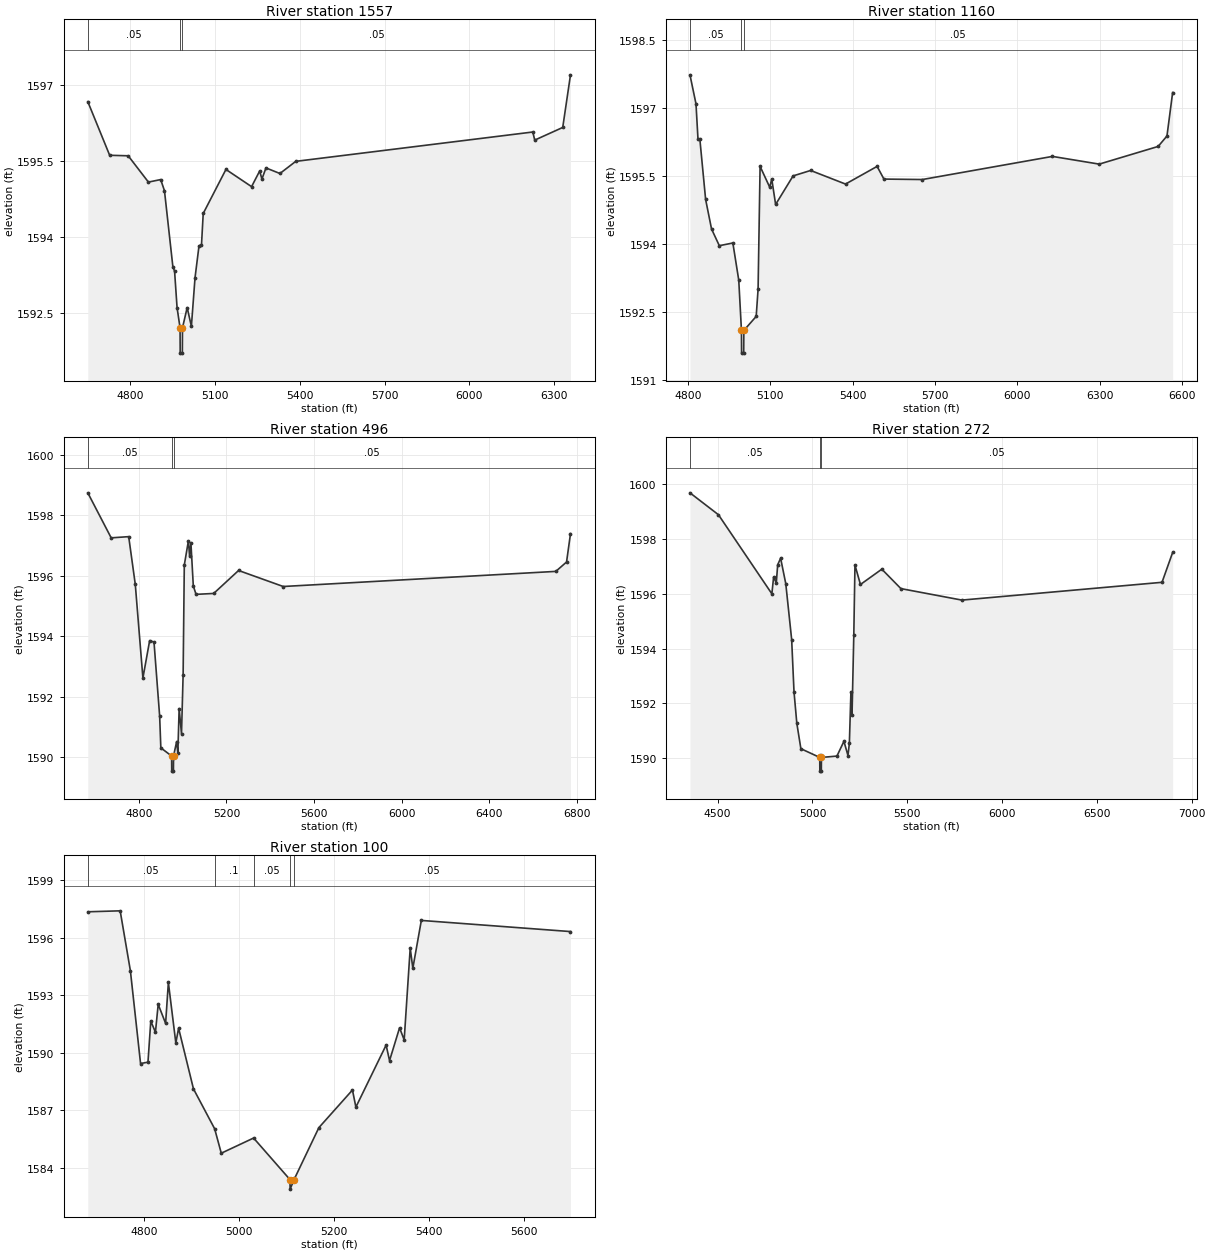
Type RM Length L Ch R = 1,1557,397,397,397
BEGIN DESCRIPTION:
Deadman 15 1.2
END DESCRIPTION:
XS GIS Cut Line= 3
      1591761.58      6903170.23      1591480.00      6902763.00
      1590541.93      6901992.88
#Sta/Elev= 30
  4649.6 1596.68  4727.0 1595.62  4792.6 1595.61  4864.2 1595.09  4907.6 1595.14
  4921.0 1594.92  4950.7 1593.42  4956.8 1593.33  4965.6 1592.61  4976.2 1592.21
  4976.7 1591.71  4984.3 1591.71  4984.8 1592.21  5001.4 1592.61  5016.3 1592.24
  5029.2 1593.20  5043.3 1593.83  5052.1 1593.85  5058.2 1594.47  5138.6 1595.34
  5229.4 1595.00  5258.1 1595.31  5266.0 1595.15  5280.3 1595.37  5329.8 1595.26
  5385.8 1595.50  6225.0 1596.08  6231.8 1595.92  6330.9 1596.17  6358.4 1597.21
#Mann=3,-1,0
  4649.6    0.05       0  4976.2    0.05       0  4984.8    0.05       0
Bank Sta=4976.2,4984.8
Exp/Cntr=0.3,0.1

Type RM Length L Ch R = 1,1160,664,664,664
BEGIN DESCRIPTION:
Deadman 15 1.4
END DESCRIPTION:
XS GIS Cut Line= 3
      1592024.58      6902839.47      1591580.00      6902363.00
      1590545.68      6901969.56
#Sta/Elev= 30
  4807.4 1597.74  4829.4 1597.10  4836.7 1596.32  4843.5 1596.32  4864.5 1594.99
  4886.0 1594.34  4914.4 1593.97  4963.7 1594.03  4985.2 1593.21  4995.0 1592.10
  4995.5 1591.60  5003.2 1591.60  5003.7 1592.10  5048.7 1592.41  5055.6 1593.01
  5062.9 1595.72  5098.0 1595.26  5105.4 1595.44  5119.5 1594.88  5183.1 1595.51
  5247.1 1595.63  5374.1 1595.33  5489.2 1595.72  5514.0 1595.44  5653.8 1595.43
  6127.8 1595.94  6298.2 1595.77  6512.9 1596.16  6545.0 1596.39  6565.7 1597.35
#Mann=3,-1,0
  4807.4    0.05       0  4995.0    0.05       0  5003.7    0.05       0
Bank Sta=4995,5003.7
Exp/Cntr=0.3,0.1

Type RM Length L Ch R = 1,496,224,224,224
BEGIN DESCRIPTION:
Deadman 15 0.8
END DESCRIPTION:
XS GIS Cut Line= 5
      1592394.40      6902784.82      1592240.74      6902524.38
      1592162.61      6902331.67      1592019.38      6902170.21
      1590558.66      6901940.75
#Sta/Elev= 30
  4566.7 1598.75  4673.5 1597.26  4753.5 1597.30  4783.6 1595.72  4818.4 1592.62
  4849.2 1593.86  4869.1 1593.81  4894.9 1591.36  4900.3 1590.31  4949.6 1590.04
  4950.1 1589.54  4957.8 1589.54  4958.3 1590.04  4972.6 1590.52  4978.0 1590.13
  4983.9 1591.61  4994.7 1590.78  5002.1 1592.73  5007.5 1596.36  5026.2 1597.16
  5031.6 1596.67  5037.8 1597.08  5048.6 1595.67  5061.1 1595.39  5141.7 1595.42
  5255.4 1596.18  5459.3 1595.65  6704.3 1596.15  6753.5 1596.46  6771.5 1597.40
#Mann=3,-1,0
  4566.7    0.05       0  4949.6    0.05       0  4958.3    0.05       0
Bank Sta=4949.6,4958.3
Exp/Cntr=0.3,0.1

Type RM Length L Ch R = 1,272,172,172,172
BEGIN DESCRIPTION:
Mapping XS 9eedcf83
END DESCRIPTION:
XS GIS Cut Line= 3
      1592639.75      6902857.94      1592130.00      6902013.00
      1590579.28      6901853.51
#Sta/Elev= 30
  4354.0 1599.69  4504.2 1598.89  4786.0 1596.00  4795.3 1596.61  4809.4 1596.40
  4816.7 1597.06  4832.2 1597.30  4859.4 1596.37  4890.4 1594.33  4902.8 1592.42
  4917.6 1591.27  4939.0 1590.34  5038.6 1590.02  5039.1 1589.52  5046.9 1589.52
  5047.4 1590.02  5129.2 1590.07  5166.1 1590.61  5187.4 1590.09  5194.8 1590.54
  5203.0 1592.42  5208.8 1591.56  5218.2 1594.51  5224.3 1597.05  5253.2 1596.34
  5365.9 1596.90  5466.5 1596.19  5788.1 1595.77  6843.7 1596.42  6899.7 1597.51
#Mann=3,-1,0
  4354.0    0.05       0  5038.6    0.05       0  5047.4    0.05       0
Bank Sta=5038.6,5047.4
Exp/Cntr=0.3,0.1

Type RM Length L Ch R = 1,100,0,0,0
BEGIN DESCRIPTION:
Deadman 15 0.5
END DESCRIPTION:
XS GIS Cut Line= 4
      1592584.49      6902461.89      1592423.03      6902188.44
      1592180.84      6901938.44      1591860.49      6901797.80
#Sta/Elev= 30
  4682.2 1597.34  4750.3 1597.39  4771.8 1594.27  4793.2 1589.44  4808.8 1589.51
  4814.7 1591.65  4824.5 1591.07  4830.3 1592.52  4845.9 1591.53  4851.7 1593.66
  4867.4 1590.51  4873.2 1591.28  4904.5 1588.12  4949.1 1586.04  4963.0 1584.77
  5031.0 1585.56  5107.4 1583.40  5107.9 1582.90  5116.2 1583.40  5168.3 1586.10
  5239.0 1588.06  5246.2 1587.17  5309.8 1590.40  5317.0 1589.59  5338.1 1591.30
  5347.8 1590.67  5360.5 1595.45  5366.0 1594.40  5383.9 1596.89  5697.7 1596.31
#Mann=5,-1,0
  4682.2    0.05       0  4949.1     0.1       0  5031.0    0.05       0
  5107.4    0.07       0  5116.2    0.05       0
Bank Sta=5107.4,5116.2
Exp/Cntr=0.3,0.1

Chan Stop Cuts=-1