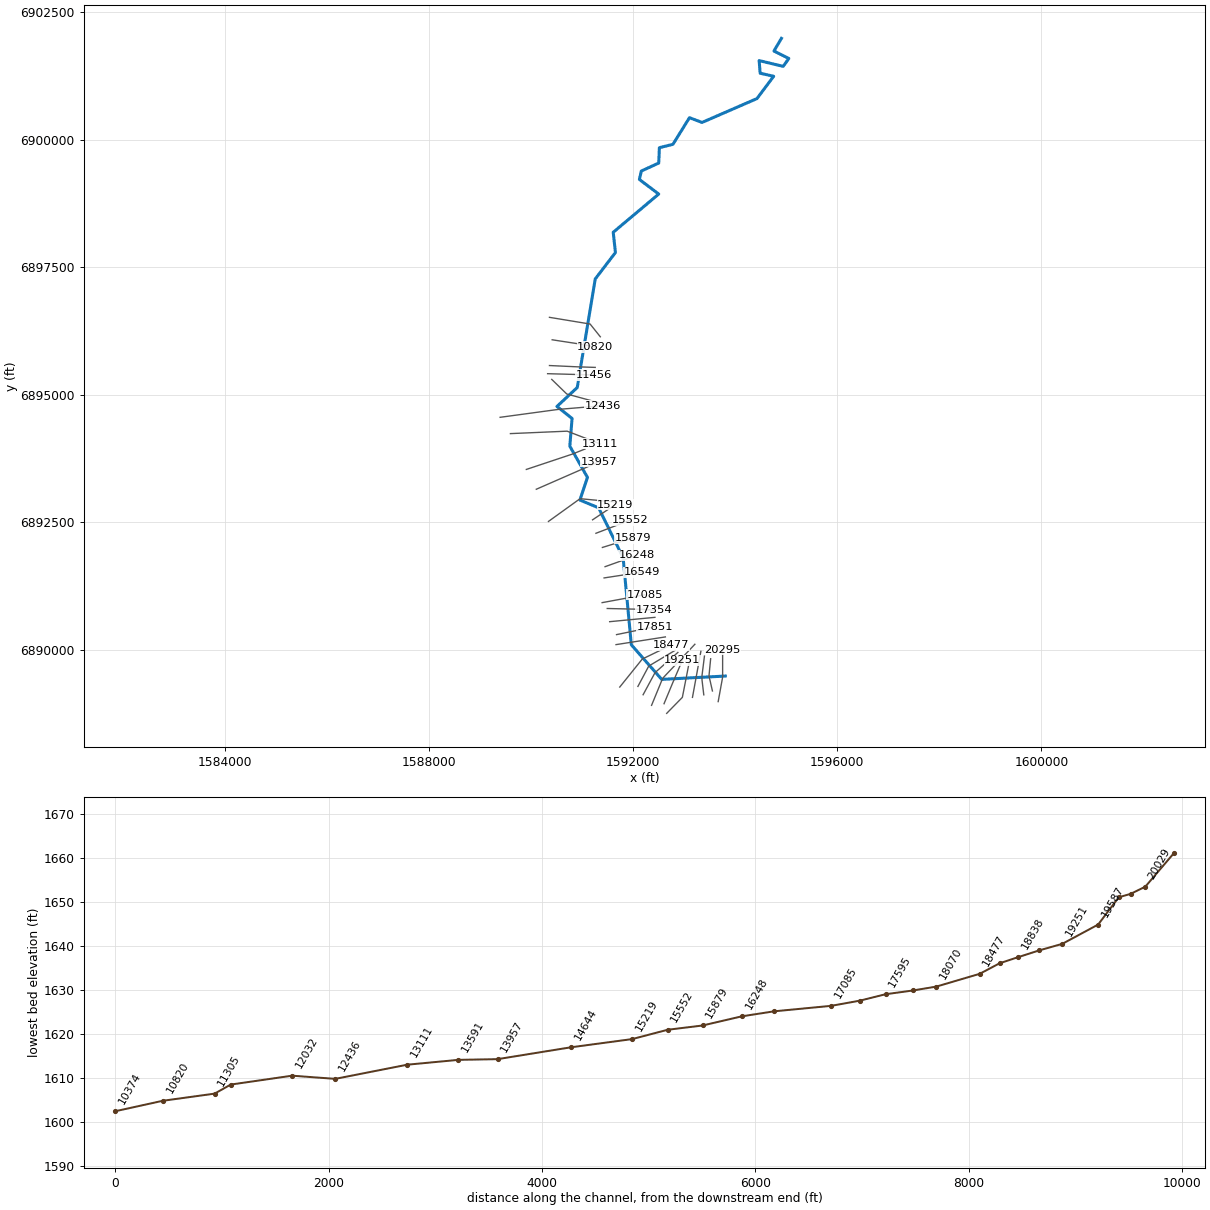
--- Deadman 16.prj (project) ---

Proj Title=Deadman 16 Base Level Engineering
Current Plan=p01
Default Exp/Contr=0.3,0.1
English Units
Geom File=g01
Flow File=f01
Plan File=p01
BEGIN DESCRIPTION:
Deadman 16
END DESCRIPTION:

--- Deadman 16.p01 (plan) ---

Plan Title=Multiple Run
Short Identifier=Multiple
Geom File=g01
Flow File=f01
Subcritical Flow
K Sum by GR= 0
Std Step Tol= 0.01
Critical Tol= 0.01
Num of Std Step Trials= 20
Max Error Tol= 0.3
Flow Tol Ratio= 0.001
Split Flow NTrial= 30
Split Flow Tol= 0.02
Split Flow Ratio= 0.02
Log Output Level= 0
Friction Slope Method= 1
Unsteady Friction Slope Method= 2
Unsteady Bridges Friction Slope Method= 1
Parabolic Critical Depth
Global Vel Dist=  1 , 1 , 1
Global Log Level= 0
CheckData=True
Encroach Param= -1, 0, 0, 0
BEGIN DESCRIPTION:
Multiple Run
END DESCRIPTION:

--- Deadman 16.f01 (steady flow) ---

Flow Title=Multiple
Number of Profiles=7
Profile Names=10-year,25-year,50-year,1pct_min,100-year,1pct_plu,500-year
River Rch & RM= Deadman 16,Reach-1,20295
      35      42      47      27      53     106      67
River Rch & RM= Deadman 16,Reach-1,18070
      70      89     103      60     119     237     160
River Rch & RM= Deadman 16,Reach-1,16248
     129     171     204     121     242     482     345
River Rch & RM= Deadman 16,Reach-1,14644
     263     362     443     269     538    1073     803
Boundary for River Rch & Prof#=Deadman 16,Reach-1,1
Up Type=0
Dn Type=3
Dn Slope=0.005
Boundary for River Rch & Prof#=Deadman 16,Reach-1,2
Up Type=0
Dn Type=3
Dn Slope=0.005
Boundary for River Rch & Prof#=Deadman 16,Reach-1,3
Up Type=0
Dn Type=3
Dn Slope=0.005
Boundary for River Rch & Prof#=Deadman 16,Reach-1,4
Up Type=0
Dn Type=3
Dn Slope=0.005
Boundary for River Rch & Prof#=Deadman 16,Reach-1,5
Up Type=0
Dn Type=3
Dn Slope=0.005
Boundary for River Rch & Prof#=Deadman 16,Reach-1,6
Up Type=0
Dn Type=3
Dn Slope=0.005
Boundary for River Rch & Prof#=Deadman 16,Reach-1,7
Up Type=0
Dn Type=3
Dn Slope=0.005

--- Deadman 16.g01 (geometry) ---

Geom Title=Existing Conditions

River Reach=Deadman 16,Reach-1
Reach XY= 30
      1593805.00      6889488.00      1592557.72      6889422.93
      1591962.76      6890100.80      1591801.83      6891807.64
      1591321.48      6892785.42      1590955.00      6892938.00
      1591103.48      6893381.60      1590757.27      6893993.94
      1590801.33      6894536.42      1590505.01      6894772.52
      1590903.03      6895143.87      1591255.68      6897272.16
      1591651.46      6897789.46      1591608.04      6898186.58
      1592499.92      6898935.72      1592121.28      6899221.26
      1592158.52      6899386.78      1592500.20      6899543.59
      1592512.68      6899844.52      1592778.91      6899910.70
      1593102.31      6900432.65      1593349.09      6900339.52
      1594425.50      6900807.17      1594753.22      6901244.21
      1594487.85      6901304.27      1594468.46      6901551.71
      1594939.42      6901438.56      1595050.23      6901593.64
      1594758.37      6901739.22      1594905.00      6901988.00

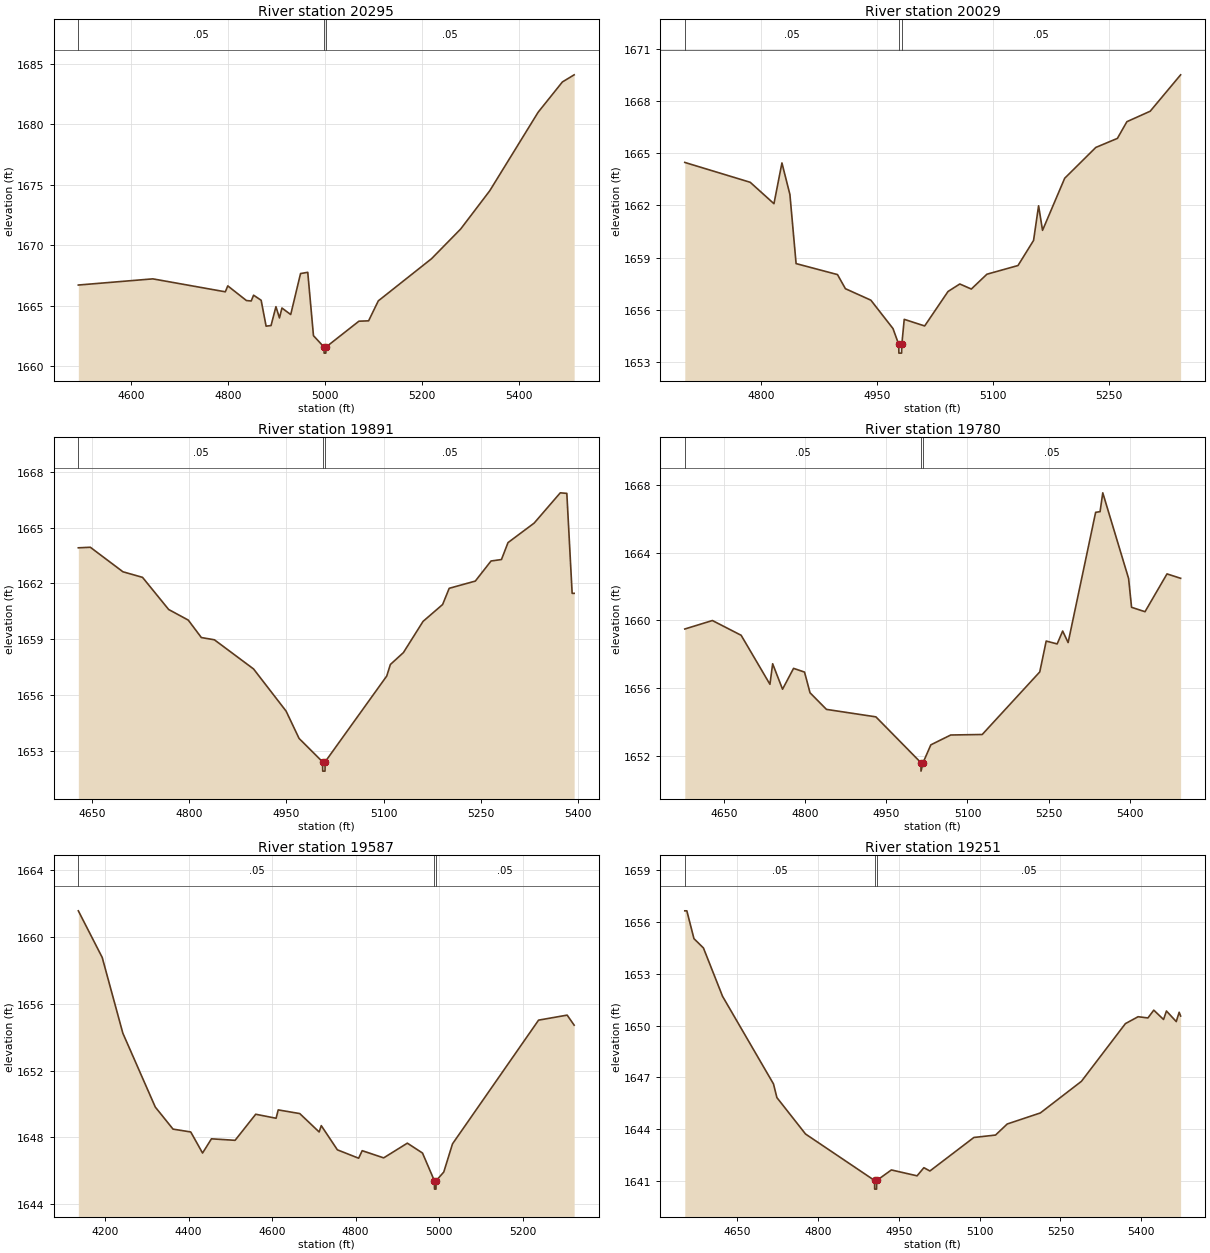
Type RM Length L Ch R = 1,20295,266,266,266
BEGIN DESCRIPTION:
Deadman 16 30.0
END DESCRIPTION:
XS GIS Cut Line= 3
      1593665.33      6888986.66      1593752.39      6889465.48
      1593752.39      6890002.31
#Sta/Elev= 30
  4491.1 1666.72  4644.9 1667.23  4794.5 1666.16  4799.6 1666.65  4838.0 1665.44
  4847.9 1665.40  4852.9 1665.88  4868.5 1665.46  4878.7 1663.32  4888.9 1663.37
  4899.0 1664.93  4906.3 1664.00  4911.4 1664.82  4929.5 1664.28  4949.8 1667.67
  4964.7 1667.77  4976.5 1662.53  4998.3 1661.59  4998.5 1661.09  5002.0 1661.09
  5002.3 1661.59  5070.3 1663.73  5090.3 1663.76  5110.3 1665.41  5220.3 1668.90
  5280.3 1671.35  5340.3 1674.51  5440.3 1681.01  5490.3 1683.51  5514.6 1684.10
#Mann=3,-1,0
  4491.1    0.05       0  4998.3    0.05       0  5002.3    0.05       0
Bank Sta=4998.3,5002.3
Exp/Cntr=0.3,0.1

Type RM Length L Ch R = 1,20029,138,138,138
BEGIN DESCRIPTION:
Mapping XS ae3fdede
END DESCRIPTION:
XS GIS Cut Line= 3
      1593552.37      6889195.59      1593485.09      6889492.93
      1593517.64      6889827.10
#Sta/Elev= 30
  4701.7 1664.47  4786.2 1663.33  4816.9 1662.10  4827.2 1664.44  4837.5 1662.63
  4845.5 1658.66  4899.0 1658.03  4909.2 1657.22  4942.1 1656.56  4970.7 1654.93
  4978.1 1654.02  4978.3 1653.52  4981.8 1653.52  4982.1 1654.02  4985.2 1655.46
  5011.6 1655.08  5041.8 1657.06  5057.0 1657.49  5071.9 1657.20  5092.0 1658.05
  5132.2 1658.55  5152.3 1659.99  5158.8 1661.98  5163.9 1660.57  5192.5 1663.56
  5232.7 1665.33  5260.6 1665.85  5272.9 1666.81  5303.0 1667.41  5342.3 1669.50
#Mann=3,-1,0
  4701.7    0.05       0  4978.1    0.05       0  4982.1    0.05       0
Bank Sta=4978.1,4982.1
Exp/Cntr=0.3,0.1

Type RM Length L Ch R = 1,19891,111,111,111
BEGIN DESCRIPTION:
Mapping XS f0b71df1
END DESCRIPTION:
XS GIS Cut Line= 4
      1593383.10      6889119.67      1593348.37      6889410.47
      1593348.37      6889499.44      1593396.12      6889879.21
#Sta/Elev= 30
  4629.4 1663.91  4647.9 1663.94  4698.2 1662.62  4728.4 1662.32  4768.7 1660.59
  4798.9 1660.02  4819.1 1659.08  4839.2 1658.96  4899.6 1657.39  4949.8 1655.12
  4969.8 1653.65  5006.0 1652.39  5006.3 1651.89  5009.8 1651.89  5010.0 1652.39
  5105.0 1657.01  5110.6 1657.63  5130.7 1658.27  5161.0 1659.95  5191.2 1660.86
  5201.3 1661.73  5241.6 1662.12  5265.8 1663.20  5281.9 1663.28  5292.0 1664.19
  5332.3 1665.24  5372.6 1666.87  5382.7 1666.84  5390.9 1661.46  5394.0 1661.46
#Mann=3,-1,0
  4629.4    0.05       0  5006.0    0.05       0  5010.0    0.05       0
Bank Sta=5006,5010
Exp/Cntr=0.3,0.1

Type RM Length L Ch R = 1,19780,193,193,193
BEGIN DESCRIPTION:
Mapping XS fc2a0b70
END DESCRIPTION:
XS GIS Cut Line= 2
      1593161.32      6889070.02      1593326.24      6889972.78
#Sta/Elev= 30
  4576.8 1659.49  4627.9 1659.99  4681.1 1659.12  4734.4 1656.23  4739.4 1657.44
  4757.7 1655.94  4778.1 1657.17  4798.4 1656.95  4808.6 1655.73  4839.0 1654.75
  4930.5 1654.31  5013.8 1651.61  5014.0 1651.11  5017.8 1651.61  5032.2 1652.66
  5069.0 1653.24  5127.3 1653.27  5233.8 1656.96  5245.7 1658.78  5266.0 1658.61
  5276.2 1659.37  5286.3 1658.69  5337.2 1666.37  5345.4 1666.41  5350.4 1667.52
  5398.2 1662.47  5403.7 1660.77  5428.6 1660.51  5469.3 1662.74  5494.5 1662.48
#Mann=3,-1,0
  4576.8    0.05       0  5013.8    0.05       0  5017.8    0.05       0
Bank Sta=5013.8,5017.8
Exp/Cntr=0.3,0.1

Type RM Length L Ch R = 1,19587,336,336,336
BEGIN DESCRIPTION:
Mapping XS 773ede81
END DESCRIPTION:
XS GIS Cut Line= 3
      1592655.82      6888756.42      1592963.25      6889070.46
      1593106.75      6889804.49
#Sta/Elev= 30
  4136.0 1661.56  4193.2 1658.77  4242.6 1654.24  4320.3 1649.82  4362.8 1648.50
  4405.2 1648.33  4433.5 1647.07  4454.8 1647.92  4511.4 1647.83  4560.8 1649.39
  4609.6 1649.15  4614.7 1649.65  4666.3 1649.43  4712.7 1648.33  4717.8 1648.71
  4756.4 1647.26  4807.3 1646.76  4815.8 1647.21  4867.3 1646.78  4923.9 1647.66
  4960.2 1647.07  4988.7 1645.41  4989.0 1644.91  4992.5 1644.91  4992.7 1645.41
  5011.1 1645.93  5032.1 1647.62  5238.2 1655.02  5306.6 1655.32  5323.4 1654.72
#Mann=3,-1,0
  4136.0    0.05       0  4988.7    0.05       0  4992.7    0.05       0
Bank Sta=4988.7,4992.7
Exp/Cntr=0.3,0.1

Type RM Length L Ch R = 1,19251,218,218,218
BEGIN DESCRIPTION:
Mapping XS 0eadbe2a
END DESCRIPTION:
XS GIS Cut Line= 3
      1592604.01      6888946.03      1592775.46      6889358.39
      1592961.76      6889793.83
#Sta/Elev= 30
  4552.9 1656.64  4556.7 1656.64  4569.9 1655.03  4587.5 1654.49  4623.0 1651.69
  4717.5 1646.62  4723.8 1645.83  4777.0 1643.72  4905.1 1641.03  4905.3 1640.53
  4908.8 1640.53  4909.1 1641.03  4936.3 1641.64  4984.0 1641.30  4996.6 1641.77
  5007.8 1641.58  5089.4 1643.52  5129.6 1643.66  5151.3 1644.30  5212.8 1644.94
  5289.0 1646.77  5370.6 1650.11  5394.2 1650.51  5412.4 1650.44  5423.3 1650.89
  5441.4 1650.35  5446.8 1650.84  5465.0 1650.23  5470.4 1650.77  5473.1 1650.55
#Mann=3,-1,0
  4552.9    0.05       0  4905.1    0.03       0  4909.1    0.05       0
Bank Sta=4905.1,4909.1
Exp/Cntr=0.3,0.1

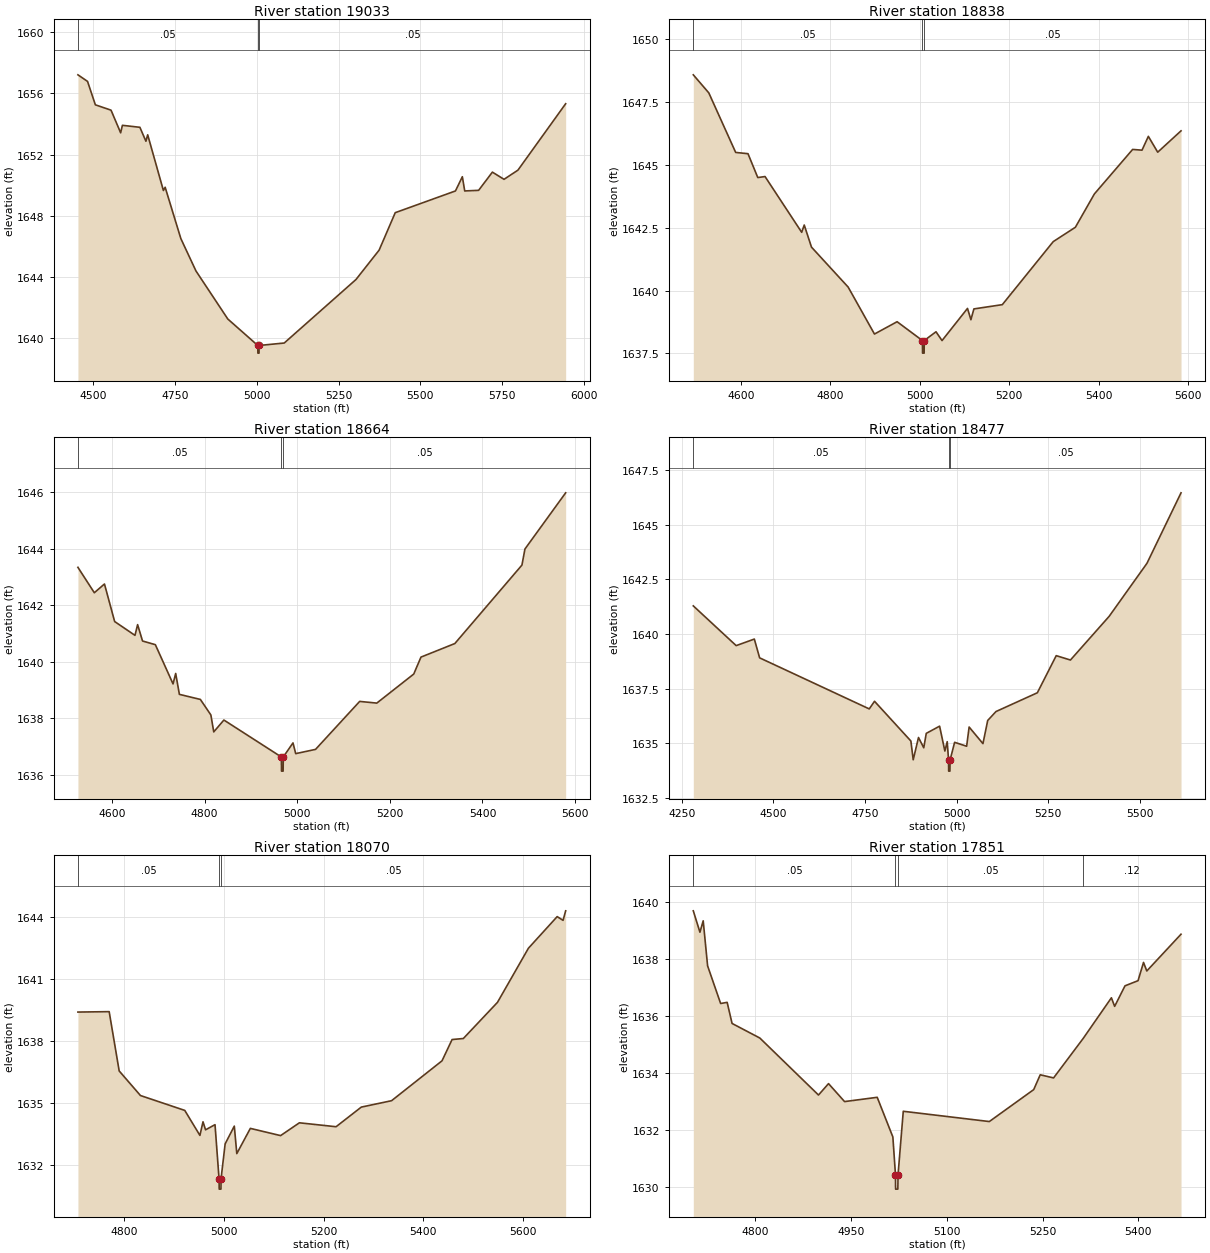
Type RM Length L Ch R = 1,19033,195,195,195
BEGIN DESCRIPTION:
Deadman 16 29.0
END DESCRIPTION:
XS GIS Cut Line= 3
      1592359.54      6888914.17      1592577.16      6889443.72
      1593208.30      6890111.13
#Sta/Elev= 30
  4453.3 1657.22  4482.7 1656.79  4506.6 1655.26  4554.5 1654.91  4583.9 1653.43
  4589.3 1653.92  4642.7 1653.79  4661.2 1652.88  4666.6 1653.30  4714.6 1649.66
  4720.0 1649.87  4767.9 1646.52  4814.2 1644.40  4911.5 1641.26  5003.2 1639.53
  5003.5 1639.03  5007.0 1639.03  5007.2 1639.53  5084.0 1639.69  5303.3 1643.84
  5374.1 1645.76  5423.4 1648.21  5607.5 1649.63  5628.6 1650.56  5635.8 1649.63
  5678.3 1649.67  5720.4 1650.86  5756.0 1650.39  5798.5 1650.99  5944.4 1655.33
#Mann=3,-1,0
  4453.3    0.05       0  5003.2    0.03       0  5007.2    0.05       0
Bank Sta=5003.2,5007.2
Exp/Cntr=0.3,0.1

Type RM Length L Ch R = 1,18838,174,174,174
BEGIN DESCRIPTION:
Mapping XS 0f2b517e
END DESCRIPTION:
XS GIS Cut Line= 3
      1592193.86      6889121.85      1592428.23      6889555.87
      1592875.29      6889950.84
#Sta/Elev= 30
  4493.9 1648.59  4528.6 1647.87  4588.6 1645.50  4616.1 1645.45  4638.0 1644.50
  4654.2 1644.54  4736.1 1642.32  4741.8 1642.61  4758.0 1641.73  4839.9 1640.14
  4898.7 1638.27  4949.3 1638.76  5005.9 1638.01  5006.2 1637.51  5009.7 1637.51
  5009.9 1638.01  5036.2 1638.36  5049.7 1638.01  5106.6 1639.29  5114.2 1638.84
  5120.9 1639.27  5184.4 1639.44  5298.2 1641.95  5347.6 1642.52  5390.2 1643.85
  5475.6 1645.62  5496.5 1645.59  5510.7 1646.14  5531.6 1645.51  5583.7 1646.36
#Mann=3,-1,0
  4493.9    0.05       0  5005.9    0.05       0  5009.9    0.05       0
Bank Sta=5005.9,5009.9
Exp/Cntr=0.3,0.1

Type RM Length L Ch R = 1,18664,187,187,187
BEGIN DESCRIPTION:
Mapping XS 6ac7ad65
END DESCRIPTION:
XS GIS Cut Line= 3
      1592091.87      6889284.62      1592304.54      6889683.91
      1592820.49      6889991.75
#Sta/Elev= 30
  4526.4 1643.34  4561.8 1642.44  4583.7 1642.75  4605.7 1641.42  4649.6 1640.93
  4655.3 1641.31  4665.9 1640.73  4693.6 1640.60  4731.8 1639.21  4737.5 1639.58
  4745.5 1638.84  4790.8 1638.66  4813.5 1638.11  4819.7 1637.51  4841.6 1637.93
  4965.8 1636.62  4966.0 1636.12  4969.5 1636.12  4969.8 1636.62  4990.8 1637.12
  4996.7 1636.74  5039.5 1636.89  5134.8 1638.59  5171.8 1638.53  5251.6 1639.56
  5267.2 1640.16  5340.3 1640.64  5485.2 1643.42  5491.7 1643.99  5579.6 1645.98
#Mann=3,-1,0
  4526.4    0.05       0  4965.8    0.05       0  4969.8    0.05       0
Bank Sta=4965.8,4969.8
Exp/Cntr=0.3,0.1

Type RM Length L Ch R = 1,18477,407,407,407
BEGIN DESCRIPTION:
Mapping XS 79aca421
END DESCRIPTION:
XS GIS Cut Line= 3
      1591736.11      6889272.48      1592177.09      6889821.09
      1592741.51      6890094.65
#Sta/Elev= 30
  4281.2 1641.29  4398.2 1639.47  4447.8 1639.77  4462.2 1638.91  4761.4 1636.57
  4775.8 1636.92  4875.0 1635.10  4881.4 1634.24  4895.8 1635.26  4910.2 1634.79
  4917.0 1635.45  4953.4 1635.78  4967.8 1634.64  4974.2 1635.07  4977.9 1634.22
  4978.1 1633.72  4981.6 1633.72  4981.9 1634.22  4994.4 1635.04  5027.2 1634.86
  5034.0 1635.74  5071.7 1634.98  5084.7 1636.04  5107.3 1636.45  5220.2 1637.31
  5271.7 1639.01  5310.5 1638.81  5416.1 1640.81  5519.3 1643.24  5612.3 1646.47
#Mann=3,-1,0
  4281.2    0.05       0  4977.9    0.05       0  4981.9    0.05       0
Bank Sta=4977.9,4981.9
Exp/Cntr=0.3,0.1

Type RM Length L Ch R = 1,18070,219,219,219
BEGIN DESCRIPTION:
Mapping XS 438b091c
END DESCRIPTION:
XS GIS Cut Line= 2
      1591663.17      6890104.08      1592630.15      6890255.11
#Sta/Elev= 30
  4707.0 1639.38  4769.7 1639.40  4789.8 1636.53  4832.5 1635.34  4921.4 1634.62
  4951.8 1633.41  4958.0 1634.07  4963.1 1633.68  4982.1 1633.93  4990.2 1631.31
  4990.5 1630.81  4994.0 1630.81  4994.2 1631.31  5002.4 1633.00  5020.8 1633.86
  5025.8 1632.53  5053.0 1633.75  5113.7 1633.40  5151.4 1634.02  5225.0 1633.83
  5275.6 1634.78  5336.4 1635.09  5437.6 1637.02  5457.8 1638.05  5480.4 1638.10
  5548.9 1639.85  5611.0 1642.47  5668.7 1644.00  5680.5 1643.82  5685.7 1644.28
#Mann=3,-1,0
  4707.0    0.05       0  4990.2    0.05       0  4994.2    0.05       0
Bank Sta=4990.2,4994.2
Exp/Cntr=0.3,0.1

Type RM Length L Ch R = 1,17851,256,256,256
BEGIN DESCRIPTION:
Mapping XS 12a2f640
END DESCRIPTION:
XS GIS Cut Line= 2
      1591673.06      6890300.23      1592420.89      6890454.13
#Sta/Elev= 30
  4703.2 1639.69  4713.6 1638.94  4718.7 1639.34  4725.6 1637.76  4746.0 1636.44
  4756.2 1636.48  4763.9 1635.74  4807.3 1635.23  4899.2 1633.23  4914.9 1633.63
  4940.0 1633.00  4991.1 1633.15  5015.6 1631.76  5019.7 1630.43  5019.9 1629.93
  5023.4 1629.93  5023.7 1630.43  5031.9 1632.66  5166.6 1632.30  5236.1 1633.42
  5246.3 1633.94  5267.2 1633.83  5313.4 1635.21  5357.7 1636.64  5362.8 1636.34
  5379.0 1637.06  5399.4 1637.24  5408.0 1637.88  5413.1 1637.58  5466.7 1638.87
#Mann=4,-1,0
  4703.2    0.05       0  5019.7    0.05       0  5023.7    0.05       0
  5313.4    0.12       0
Bank Sta=5019.7,5023.7
Exp/Cntr=0.3,0.1

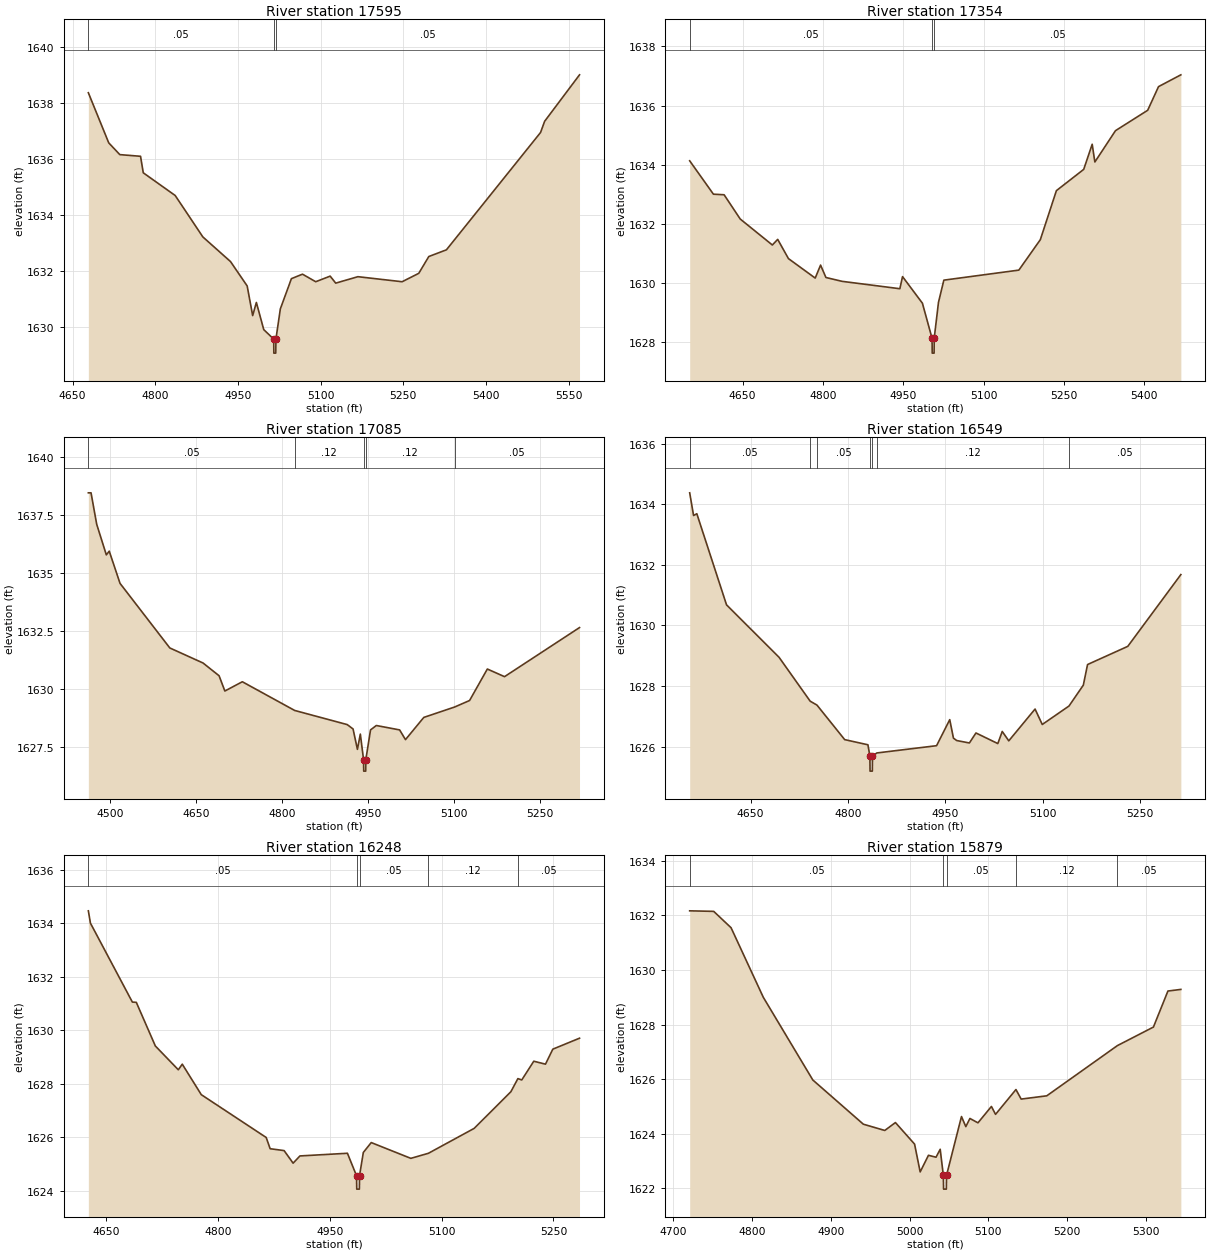
Type RM Length L Ch R = 1,17595,241,241,241
BEGIN DESCRIPTION:
Mapping XS db66ea0f
END DESCRIPTION:
XS GIS Cut Line= 2
      1591538.16      6890553.73      1592425.39      6890638.81
#Sta/Elev= 30
  4678.5 1638.38  4715.5 1636.59  4735.6 1636.17  4773.2 1636.11  4778.2 1635.52
  4836.1 1634.71  4886.3 1633.23  4936.5 1632.35  4966.7 1631.48  4976.7 1630.42
  4983.4 1630.89  4996.8 1629.92  5014.9 1629.58  5015.1 1629.08  5018.6 1629.08
  5018.9 1629.58  5026.9 1630.66  5047.0 1631.74  5067.1 1631.90  5091.1 1631.63
  5117.3 1631.83  5127.4 1631.58  5167.6 1631.81  5247.9 1631.63  5278.1 1631.93
  5296.3 1632.53  5328.3 1632.77  5499.1 1636.96  5506.5 1637.36  5569.8 1639.02
#Mann=3,-1,0
  4678.5    0.05       0  5014.9    0.05       0  5018.9    0.05       0
Bank Sta=5014.9,5018.9
Exp/Cntr=0.3,0.1

Type RM Length L Ch R = 1,17354,269,269,269
BEGIN DESCRIPTION:
Mapping XS f2f36f5a
END DESCRIPTION:
XS GIS Cut Line= 3
      1591490.73      6890812.38      1592222.07      6890795.02
      1592406.51      6890777.66
#Sta/Elev= 30
  4551.2 1634.13  4595.5 1633.00  4615.5 1632.98  4645.5 1632.16  4705.5 1631.28
  4715.5 1631.47  4735.5 1630.82  4785.5 1630.16  4795.5 1630.60  4805.5 1630.18
  4835.6 1630.05  4943.5 1629.80  4948.5 1630.21  4985.6 1629.31  5003.6 1628.12
  5003.9 1627.62  5007.4 1627.62  5007.6 1628.12  5015.6 1629.34  5025.6 1630.09
  5165.6 1630.43  5205.7 1631.46  5235.7 1633.12  5286.7 1633.84  5302.5 1634.69
  5307.5 1634.09  5346.0 1635.15  5406.1 1635.84  5426.3 1636.64  5468.0 1637.04
#Mann=3,-1,0
  4551.2    0.05       0  5003.6    0.03       0  5007.6    0.05       0
Bank Sta=5003.6,5007.6
Exp/Cntr=0.3,0.1

Type RM Length L Ch R = 1,17085,536,536,536
BEGIN DESCRIPTION:
Mapping XS 710b8a1e
END DESCRIPTION:
XS GIS Cut Line= 2
      1591390.66      6890927.00      1592233.73      6891083.13
#Sta/Elev= 30
  4461.9 1638.46  4466.6 1638.46  4476.5 1637.10  4493.3 1635.78  4498.4 1635.94
  4517.2 1634.55  4604.1 1631.76  4662.1 1631.11  4690.1 1630.56  4700.2 1629.90
  4730.7 1630.30  4822.1 1629.06  4913.8 1628.45  4924.0 1628.26  4931.6 1627.38
  4936.7 1628.04  4942.3 1626.94  4942.6 1626.44  4946.1 1626.44  4946.3 1626.94
  4954.5 1628.22  4964.6 1628.41  5005.3 1628.22  5015.5 1627.80  5047.5 1628.76
  5101.4 1629.21  5127.4 1629.49  5158.4 1630.85  5188.4 1630.52  5319.3 1632.64
#Mann=5,-1,0
  4461.9    0.05       0  4822.1    0.12       0  4942.3    0.07       0
  4946.3    0.12       0  5101.4    0.05       0
Bank Sta=4942.3,4946.3
Exp/Cntr=0.3,0.1

Type RM Length L Ch R = 1,16549,301,301,301
BEGIN DESCRIPTION:
Mapping XS dc7735e4
END DESCRIPTION:
XS GIS Cut Line= 2
      1591428.84      6891411.38      1592177.11      6891525.96
#Sta/Elev= 30
  4556.1 1634.38  4562.1 1633.63  4567.1 1633.69  4612.9 1630.68  4693.8 1628.95
  4741.8 1627.50  4752.3 1627.37  4795.0 1626.23  4830.8 1626.06  4833.8 1625.69
  4834.1 1625.19  4837.6 1625.19  4837.8 1625.69  4844.6 1625.79  4936.6 1626.03
  4956.9 1626.89  4962.6 1626.28  4967.6 1626.20  4987.2 1626.12  4997.3 1626.45
  5031.0 1626.10  5037.8 1626.50  5047.9 1626.19  5088.4 1627.24  5099.5 1626.73
  5140.7 1627.34  5162.8 1628.03  5169.3 1628.71  5231.3 1629.31  5313.1 1631.68
#Mann=7,-1,0
  4556.1    0.05       0  4741.8    0.12       0  4752.3    0.05       0
  4833.8    0.07       0  4837.8    0.05       0  4844.6    0.12       0
  5140.7    0.05       0
Bank Sta=4833.8,4837.8
Exp/Cntr=0.3,0.1

Type RM Length L Ch R = 1,16248,369,369,369
BEGIN DESCRIPTION:
Mapping XS dff595bb
END DESCRIPTION:
XS GIS Cut Line= 2
      1591447.96      6891631.87      1592067.93      6891853.54
#Sta/Elev= 30
  4626.5 1634.46  4629.3 1634.00  4685.5 1631.05  4690.8 1631.04  4716.3 1629.41
  4747.1 1628.52  4752.4 1628.73  4777.9 1627.59  4864.9 1625.99  4870.2 1625.57
  4888.9 1625.50  4901.0 1625.03  4910.1 1625.30  4973.8 1625.40  4986.0 1624.56
  4986.3 1624.06  4989.8 1624.06  4990.0 1624.56  4995.1 1625.43  5005.7 1625.80
  5058.8 1625.21  5082.4 1625.40  5143.7 1626.33  5192.9 1627.70  5202.3 1628.19
  5207.5 1628.14  5223.6 1628.84  5239.3 1628.73  5249.1 1629.29  5284.9 1629.70
#Mann=5,-1,0
  4626.5    0.05       0  4986.0    0.05       0  4990.0    0.05       0
  5082.4    0.12       0  5202.3    0.05       0
Bank Sta=4986,4990
Exp/Cntr=0.3,0.1

Type RM Length L Ch R = 1,15879,327,327,327
BEGIN DESCRIPTION:
Mapping XS efec89d4
END DESCRIPTION:
XS GIS Cut Line= 2
      1591395.87      6892008.61      1591990.70      6892194.17
#Sta/Elev= 30
  4721.1 1632.17  4751.6 1632.15  4773.6 1631.55  4814.5 1629.00  4877.3 1625.97
  4941.4 1624.35  4968.6 1624.12  4982.1 1624.41  5006.4 1623.62  5013.5 1622.60
  5024.0 1623.21  5033.6 1623.14  5038.9 1623.43  5042.9 1622.47  5043.2 1621.97
  5046.7 1621.97  5046.9 1622.47  5065.9 1624.63  5071.4 1624.26  5076.6 1624.56
  5086.8 1624.40  5103.9 1625.00  5109.1 1624.71  5135.0 1625.62  5141.6 1625.27
  5174.1 1625.39  5263.7 1627.23  5309.4 1627.91  5327.8 1629.23  5344.2 1629.29
#Mann=5,-1,0
  4721.1    0.05       0  5042.9    0.05       0  5046.9    0.05       0
  5135.0    0.12       0  5263.7    0.05       0
Bank Sta=5042.9,5046.9
Exp/Cntr=0.3,0.1

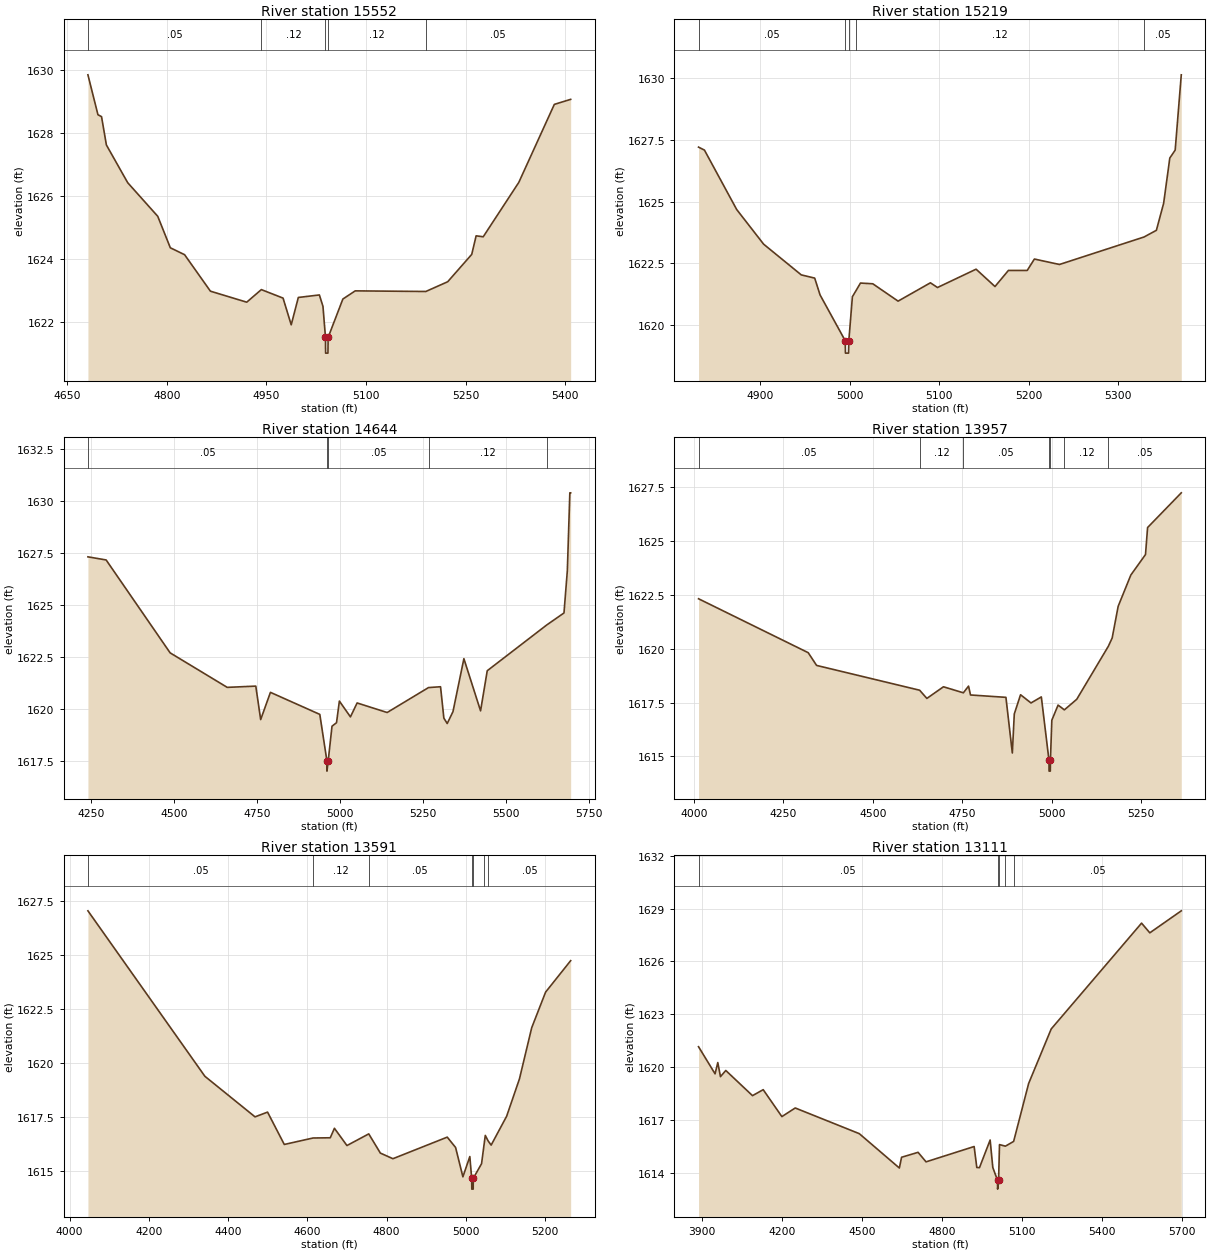
Type RM Length L Ch R = 1,15552,333,333,333
BEGIN DESCRIPTION:
Mapping XS 90561e2a
END DESCRIPTION:
XS GIS Cut Line= 2
      1591269.09      6892286.37      1591947.95      6892546.80
#Sta/Elev= 30
  4681.1 1629.85  4696.2 1628.58  4701.6 1628.52  4708.9 1627.62  4741.0 1626.42
  4786.3 1625.35  4805.2 1624.35  4826.7 1624.13  4865.6 1622.97  4920.3 1622.62
  4942.3 1623.02  4975.0 1622.75  4987.3 1621.90  4998.0 1622.77  5029.7 1622.85
  5035.1 1622.49  5038.9 1621.50  5039.1 1621.00  5042.6 1621.00  5042.9 1621.50
  5065.1 1622.72  5083.7 1622.98  5190.0 1622.96  5223.0 1623.27  5259.2 1624.14
  5265.8 1624.73  5276.5 1624.70  5330.1 1626.43  5383.6 1628.91  5408.2 1629.07
#Mann=5,-1,0
  4681.1    0.05       0  4942.3    0.12       0  5038.9    0.07       0
  5042.9    0.12       0  5190.0    0.05       0
Bank Sta=5038.9,5042.9
Exp/Cntr=0.3,0.1

Type RM Length L Ch R = 1,15219,575,575,575
BEGIN DESCRIPTION:
Mapping XS dc863c16
END DESCRIPTION:
XS GIS Cut Line= 2
      1591203.14      6892550.27      1591651.35      6892849.65
#Sta/Elev= 30
  4831.3 1627.20  4837.9 1627.08  4873.9 1624.68  4904.0 1623.28  4946.0 1622.04
  4961.0 1621.91  4967.0 1621.23  4995.1 1619.38  4995.3 1618.88  4998.8 1618.88
  4999.1 1619.38  5003.1 1621.16  5007.4 1621.42  5012.1 1621.71  5025.9 1621.68
  5054.1 1620.98  5090.2 1621.72  5098.1 1621.53  5141.2 1622.27  5162.3 1621.57
  5177.3 1622.22  5198.3 1622.22  5206.3 1622.68  5234.3 1622.46  5328.7 1623.57
  5342.5 1623.84  5350.6 1624.93  5357.5 1626.76  5363.5 1627.08  5370.3 1630.12
#Mann=5,-1,0
  4831.3    0.05       0  4995.1    0.05       0  4999.1    0.05       0
  5007.4    0.12       0  5328.7    0.05       0
Bank Sta=4995.1,4999.1
Exp/Cntr=0.3,0.1

Type RM Length L Ch R = 1,14644,687,687,687
BEGIN DESCRIPTION:
Deadman 16 19.0
END DESCRIPTION:
XS GIS Cut Line= 3
      1590338.59      6892518.84      1590958.13      6892964.57
      1591644.99      6892900.09
#Sta/Elev= 30
  4240.7 1627.32  4295.5 1627.17  4488.2 1622.70  4660.0 1621.04  4746.0 1621.10
  4760.7 1619.49  4790.1 1620.80  4938.7 1619.74  4960.0 1617.51  4960.2 1617.01
  4964.0 1617.51  4975.4 1619.17  4989.0 1619.34  4997.6 1620.38  5030.9 1619.62
  5051.0 1620.29  5141.4 1619.83  5265.9 1621.03  5302.1 1621.07  5312.1 1619.56
  5322.2 1619.30  5339.5 1619.87  5372.4 1622.42  5422.6 1619.91  5442.7 1621.84
  5621.6 1624.04  5673.7 1624.62  5683.8 1626.66  5691.3 1630.40  5693.8 1630.40
#Mann=5,-1,0
  4240.7    0.05       0  4960.0    0.05       0  4964.0    0.05       0
  5265.9    0.12       0  5621.6    0.05       0
Bank Sta=4960,4964
Exp/Cntr=0.3,0.1

Type RM Length L Ch R = 1,13957,366,366,366
BEGIN DESCRIPTION:
Mapping XS 38255725
END DESCRIPTION:
XS GIS Cut Line= 2
      1590100.28      6893149.60      1591336.57      6893690.65
#Sta/Elev= 30
  4012.7 1622.31  4319.3 1619.81  4342.7 1619.22  4630.8 1618.07  4651.0 1617.69
  4697.4 1618.23  4753.0 1617.95  4767.5 1618.26  4773.0 1617.85  4872.0 1617.74
  4889.9 1615.16  4895.4 1616.97  4912.9 1617.86  4942.1 1617.48  4971.0 1617.76
  4992.4 1614.82  4992.6 1614.32  4996.1 1614.32  4996.4 1614.82  5000.3 1616.68
  5017.8 1617.38  5035.4 1617.16  5070.0 1617.65  5158.4 1620.11  5169.0 1620.49
  5185.8 1621.96  5221.2 1623.41  5262.2 1624.36  5268.0 1625.61  5362.2 1627.22
#Mann=7,-1,0
  4012.7    0.05       0  4630.8    0.12       0  4753.0    0.05       0
  4992.4    0.05       0  4996.4    0.05       0  5035.4    0.12       0
  5158.4    0.05       0
Bank Sta=4992.4,4996.4
Exp/Cntr=0.3,0.1

Type RM Length L Ch R = 1,13591,480,480,480
BEGIN DESCRIPTION:
Deadman 16 18.0
END DESCRIPTION:
XS GIS Cut Line= 3
      1589905.02      6893538.01      1590805.00      6893838.00
      1591054.98      6893937.99
#Sta/Elev= 30
  4046.4 1627.06  4341.5 1619.39  4468.0 1617.51  4499.6 1617.73  4541.8 1616.23
  4614.5 1616.53  4657.8 1616.54  4668.3 1616.98  4699.9 1616.18  4754.9 1616.72
  4784.2 1615.83  4815.9 1615.57  4952.9 1616.57  4974.0 1616.09  4992.4 1614.73
  5009.9 1615.67  5014.6 1614.66  5014.9 1614.16  5018.4 1614.16  5018.6 1614.66
  5039.5 1615.34  5045.3 1616.15  5048.9 1616.65  5056.2 1616.39  5063.7 1616.20
  5102.8 1617.54  5135.1 1619.27  5166.0 1621.64  5201.0 1623.29  5264.3 1624.75
#Mann=7,-1,0
  4046.4    0.05       0  4614.5    0.12       0  4754.9    0.05       0
  5014.6    0.05       0  5018.6    0.05       0  5045.3    0.12       0
  5056.2    0.05       0
Bank Sta=5014.6,5018.6
Exp/Cntr=0.3,0.1

Type RM Length L Ch R = 1,13111,675,675,675
BEGIN DESCRIPTION:
Deadman 16 17.0
END DESCRIPTION:
XS GIS Cut Line= 3
      1589592.87      6894240.12      1590705.00      6894288.00
      1591355.02      6894037.99
#Sta/Elev= 30
  3887.0 1621.15  3949.0 1619.61  3959.2 1620.25  3969.2 1619.45  3989.2 1619.80
  4089.3 1618.37  4129.4 1618.71  4199.4 1617.18  4249.5 1617.67  4489.7 1616.21
  4639.8 1614.26  4648.1 1614.87  4709.9 1615.15  4739.9 1614.61  4920.1 1615.48
  4930.1 1614.29  4940.1 1614.28  4980.1 1615.85  4990.1 1614.29  5007.8 1613.56
  5008.1 1613.06  5011.8 1613.56  5015.2 1615.59  5037.3 1615.50  5068.2 1615.77
  5124.4 1619.06  5209.1 1622.16  5547.7 1628.17  5578.7 1627.62  5696.6 1628.87
#Mann=5,-1,0
  3887.0    0.05       0  5007.8    0.05       0  5011.8    0.05       0
  5037.3    0.12       0  5068.2    0.05       0
Bank Sta=5007.8,5011.8
Exp/Cntr=0.3,0.1

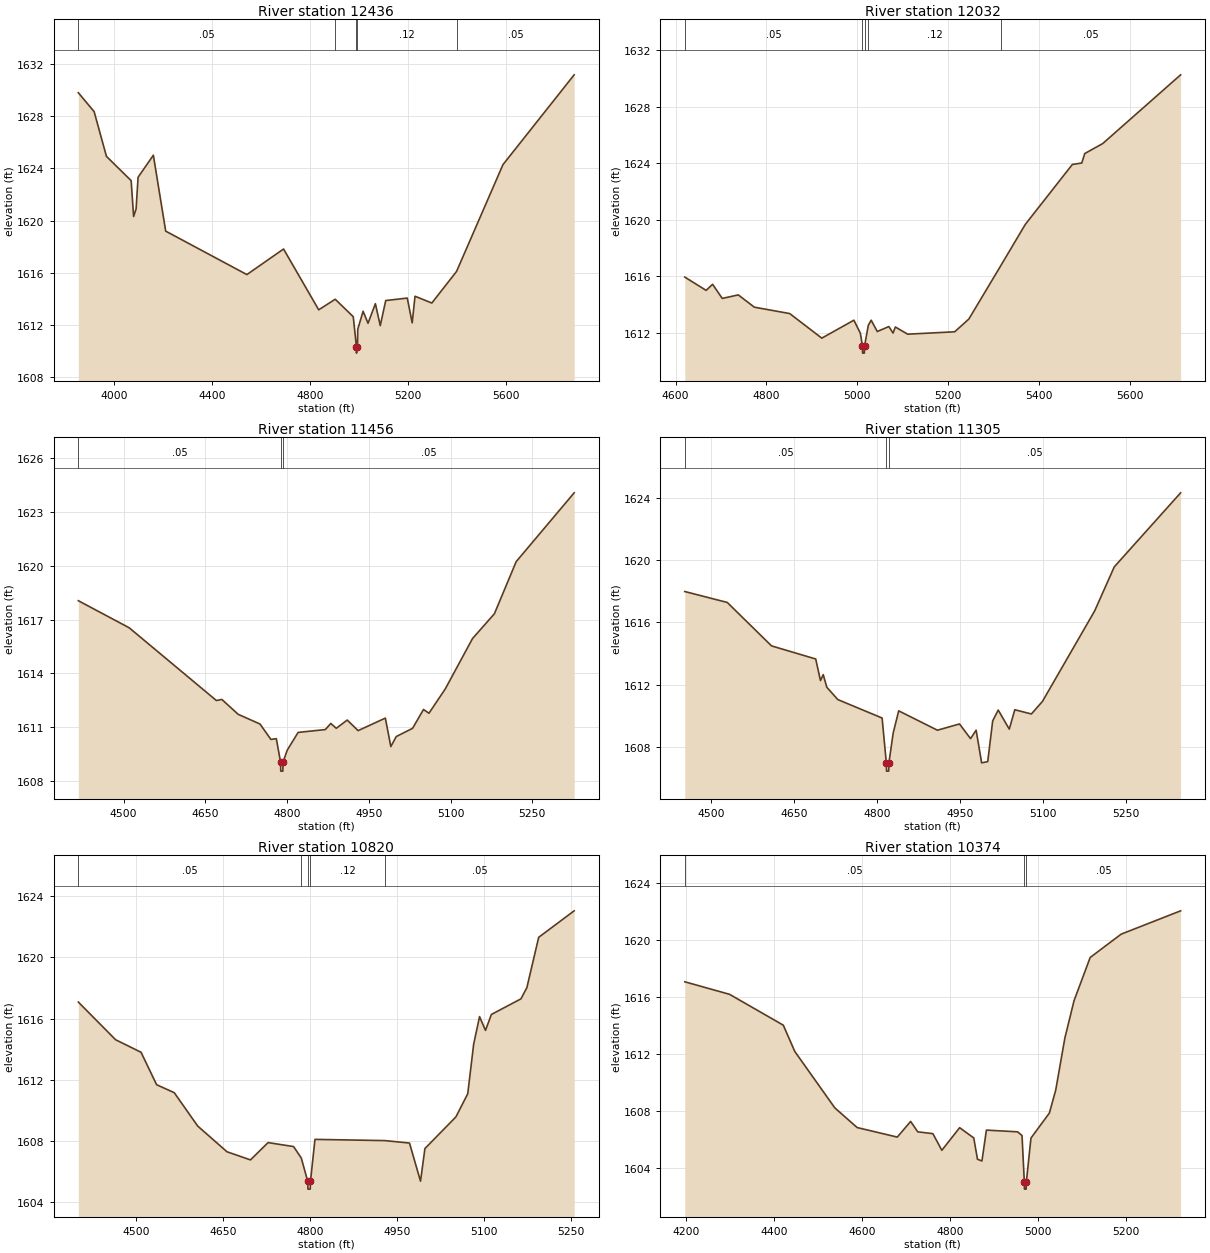
Type RM Length L Ch R = 1,12436,404,404,404
BEGIN DESCRIPTION:
Deadman 16 16.0
END DESCRIPTION:
XS GIS Cut Line= 3
      1589391.00      6894559.71      1590526.40      6894713.90
      1591404.96      6894788.00
#Sta/Elev= 30
  3852.3 1629.80  3916.9 1628.35  3967.3 1624.92  4068.3 1623.06  4078.4 1620.31
  4088.5 1620.89  4096.6 1623.32  4159.1 1625.01  4209.6 1619.19  4541.5 1615.86
  4691.5 1617.82  4835.2 1613.16  4902.8 1613.97  4976.5 1612.63  4989.4 1610.34
  4989.7 1609.84  4993.8 1610.34  4994.9 1611.67  5016.8 1613.05  5036.9 1612.13
  5067.0 1613.63  5087.0 1611.95  5109.3 1613.87  5197.4 1614.06  5217.5 1612.16
  5229.0 1614.20  5297.8 1613.68  5398.9 1616.10  5588.8 1624.29  5879.8 1631.17
#Mann=5,-1,0
  3852.3    0.05       0  4902.8    0.12       0  4989.4    0.07       0
  4993.8    0.12       0  5398.9    0.05       0
Bank Sta=4989.4,4993.8
Exp/Cntr=0.3,0.1

Type RM Length L Ch R = 1,12032,576,576,576
BEGIN DESCRIPTION:
Deadman 16 15.0
END DESCRIPTION:
XS GIS Cut Line= 3
      1590403.02      6895302.64      1590697.41      6895016.67
      1591355.05      6894837.99
#Sta/Elev= 30
  4620.1 1615.94  4667.1 1615.00  4681.3 1615.43  4702.6 1614.43  4737.9 1614.68
  4773.3 1613.81  4851.1 1613.36  4921.8 1611.62  4992.5 1612.89  5006.7 1611.97
  5011.4 1611.06  5011.7 1610.56  5015.5 1610.56  5015.9 1611.06  5024.2 1612.52
  5030.5 1612.89  5044.0 1612.09  5069.5 1612.44  5078.7 1611.98  5083.8 1612.41
  5110.9 1611.90  5214.5 1612.07  5245.6 1612.97  5316.2 1616.76  5370.0 1619.67
  5473.6 1623.91  5494.3 1624.01  5500.9 1624.68  5540.6 1625.39  5712.0 1630.25
#Mann=5,-1,0
  4620.1    0.05       0  5011.4    0.05       0  5015.9    0.05       0
  5024.2    0.12       0  5316.2    0.05       0
Bank Sta=5011.4,5015.9
Exp/Cntr=0.3,0.1

Type RM Length L Ch R = 1,11456,151,151,151
BEGIN DESCRIPTION:
Mapping XS ea77568c
END DESCRIPTION:
XS GIS Cut Line= 2
      1590321.74      6895414.75      1591231.39      6895389.56
#Sta/Elev= 30
  4416.9 1618.05  4510.2 1616.54  4670.3 1612.48  4680.3 1612.54  4710.3 1611.71
  4750.3 1611.17  4770.3 1610.31  4780.3 1610.35  4788.1 1609.04  4788.4 1608.54
  4792.3 1608.54  4792.6 1609.04  4800.3 1609.71  4820.3 1610.70  4870.3 1610.86
  4880.3 1611.20  4890.3 1610.93  4910.4 1611.39  4930.4 1610.80  4980.4 1611.50
  4990.4 1609.91  5000.4 1610.47  5030.4 1610.93  5050.4 1611.98  5060.4 1611.77
  5090.4 1613.13  5140.4 1615.94  5180.5 1617.32  5220.5 1620.23  5326.9 1624.07
#Mann=3,-1,0
  4416.9    0.05       0  4788.1    0.05       0  4792.6    0.05       0
Bank Sta=4788.1,4792.6
Exp/Cntr=0.3,0.1

Type RM Length L Ch R = 1,11305,485,485,485
BEGIN DESCRIPTION:
Deadman 16 14.0
END DESCRIPTION:
XS GIS Cut Line= 3
      1590358.21      6895574.55      1590902.06      6895549.32
      1591255.04      6895538.00
#Sta/Elev= 30
  4452.1 1617.98  4529.0 1617.28  4609.1 1614.50  4689.1 1613.66  4697.7 1612.28
  4702.7 1612.66  4709.2 1611.85  4729.2 1611.06  4809.3 1609.88  4817.0 1606.98
  4817.3 1606.48  4821.2 1606.48  4821.5 1606.98  4829.3 1608.91  4839.3 1610.34
  4909.4 1609.10  4949.4 1609.50  4969.4 1608.56  4979.5 1609.10  4989.5 1607.01
  5000.5 1607.09  5009.5 1609.70  5019.5 1610.39  5039.5 1609.17  5049.5 1610.41
  5079.5 1610.14  5099.5 1610.94  5194.1 1616.74  5229.6 1619.56  5349.7 1624.30
#Mann=3,-1,0
  4452.1    0.05       0  4817.0    0.05       0  4821.5    0.05       0
Bank Sta=4817,4821.5
Exp/Cntr=0.3,0.1

Type RM Length L Ch R = 1,10820,446,446,446
BEGIN DESCRIPTION:
Deadman 16 13.0
END DESCRIPTION:
XS GIS Cut Line= 3
      1590411.43      6896079.16      1591005.00      6895988.00
      1591255.02      6895938.00
#Sta/Elev= 30
  4400.6 1617.08  4464.9 1614.62  4508.8 1613.80  4535.7 1611.68  4566.1 1611.16
  4606.6 1608.98  4657.1 1607.30  4697.6 1606.77  4728.0 1607.90  4772.0 1607.64
  4785.3 1606.89  4796.5 1605.36  4796.8 1604.86  4800.7 1604.86  4801.1 1605.36
  4808.9 1608.11  4929.3 1608.03  4972.0 1607.87  4991.0 1605.38  4998.6 1607.51
  5052.1 1609.58  5072.5 1611.09  5082.7 1614.33  5092.9 1616.13  5103.1 1615.23
  5113.3 1616.27  5164.3 1617.29  5174.5 1618.02  5194.9 1621.31  5256.1 1623.04
#Mann=5,-1,0
  4400.6    0.05       0  4785.3    0.12       0  4796.5    0.05       0
  4801.1    0.12       0  4929.3    0.05       0
Bank Sta=4796.5,4801.1
Exp/Cntr=0.3,0.1

Type RM Length L Ch R = 1,10374,414,414,414
BEGIN DESCRIPTION:
Deadman 16 12.0
END DESCRIPTION:
XS GIS Cut Line= 3
      1590358.18      6896519.30      1591155.00      6896388.00
      1591354.98      6896138.02
#Sta/Elev= 30
  4197.0 1617.06  4298.7 1616.18  4421.0 1614.01  4447.2 1612.16  4538.3 1608.19
  4589.0 1606.81  4680.3 1606.14  4710.7 1607.24  4726.8 1606.51  4761.3 1606.38
  4781.6 1605.21  4822.1 1606.80  4854.2 1606.08  4862.7 1604.58  4872.8 1604.46
  4883.0 1606.63  4953.9 1606.51  4964.0 1606.25  4969.2 1602.98  4969.5 1602.48
  4973.4 1602.48  4973.8 1602.98  4984.3 1606.07  5026.2 1607.83  5040.6 1609.44
  5061.4 1613.10  5082.2 1615.72  5119.0 1618.77  5189.5 1620.41  5324.7 1622.05
#Mann=3,-1,0
  4197.0    0.05       0  4969.2    0.05       0  4973.8    0.05       0
Bank Sta=4969.2,4973.8
Exp/Cntr=0.3,0.1