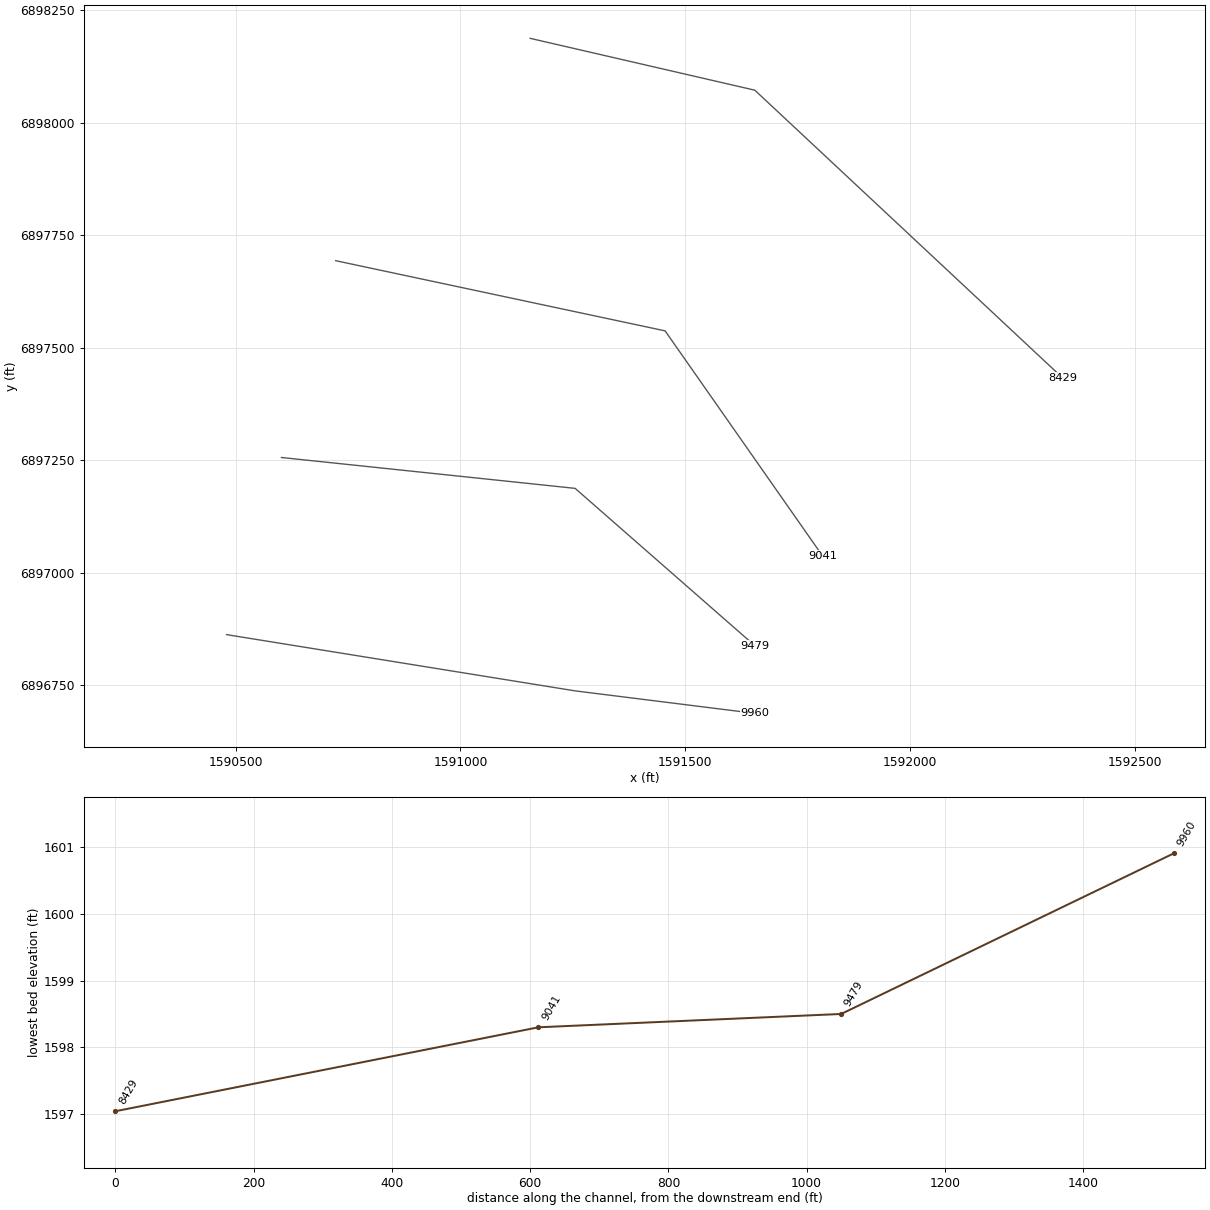
HEC-RAS study Deadman 16.prj: Deadman 16 Base Level Engineering

--- Deadman 16.g01 (geometry) --- (continued)

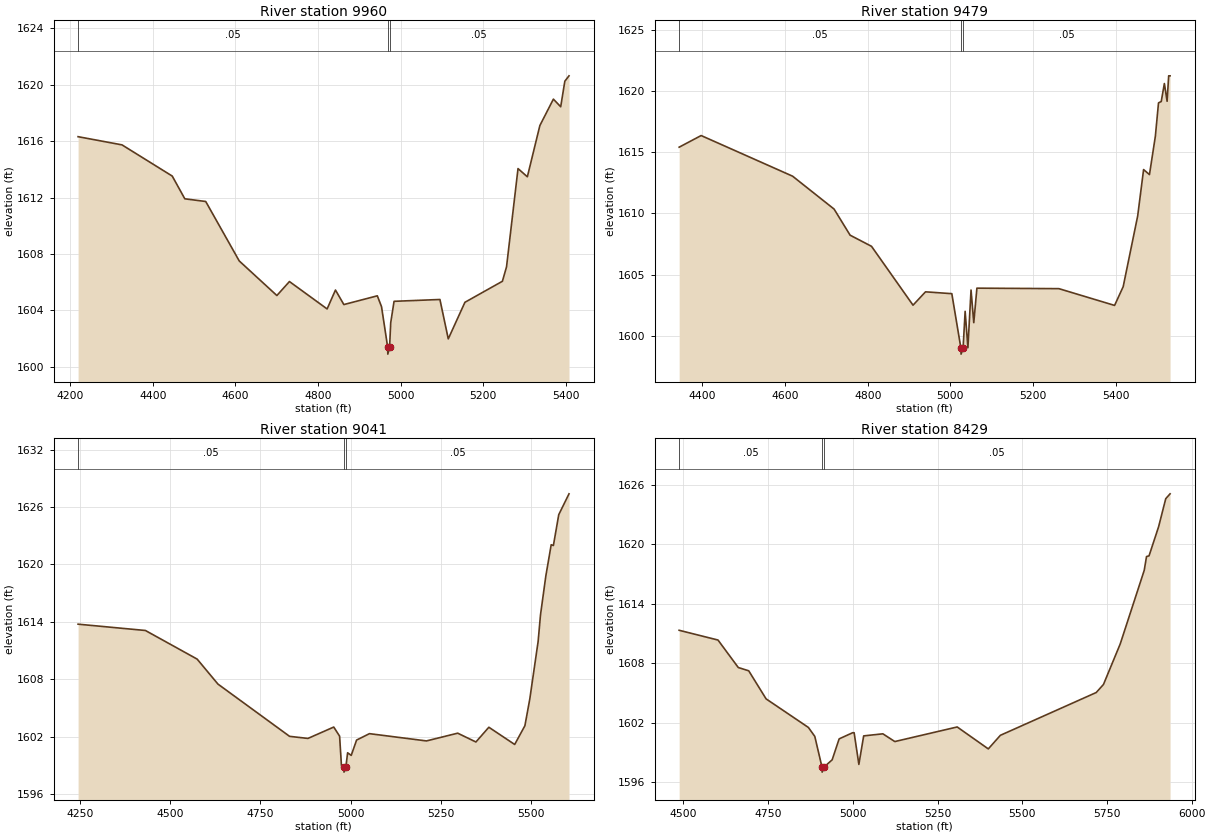
Type RM Length L Ch R = 1,9960,481,481,481
BEGIN DESCRIPTION:
Deadman 16 11.0
END DESCRIPTION:
XS GIS Cut Line= 3
      1590480.02      6896863.00      1591255.00      6896738.00
      1591654.99      6896688.00
#Sta/Elev= 30
  4219.4 1616.31  4325.7 1615.73  4447.3 1613.52  4477.7 1611.91  4528.3 1611.72
  4609.4 1607.51  4700.5 1605.06  4730.9 1606.05  4822.1 1604.11  4842.3 1605.45
  4862.6 1604.42  4943.6 1605.04  4953.8 1604.27  4968.6 1601.41  4969.0 1600.91
  4973.3 1601.41  4976.0 1603.13  4984.1 1604.65  5095.1 1604.78  5115.3 1601.99
  5155.6 1604.58  5246.3 1606.07  5256.3 1607.09  5284.1 1614.05  5306.7 1613.47
  5337.0 1617.10  5369.7 1618.97  5387.4 1618.43  5397.4 1620.24  5407.5 1620.62
#Mann=3,-1,0
  4219.4    0.05       0  4968.6    0.05       0  4973.3    0.05       0
Bank Sta=4968.6,4973.3
Exp/Cntr=0.3,0.1

Type RM Length L Ch R = 1,9479,438,438,438
BEGIN DESCRIPTION:
Deadman 16 10.0
END DESCRIPTION:
XS GIS Cut Line= 3
      1590602.05      6897256.60      1591255.00      6897188.00
      1591655.04      6896837.97
#Sta/Elev= 30
  4343.7 1615.41  4396.9 1616.36  4618.2 1613.04  4718.7 1610.35  4757.4 1608.22
  4809.2 1607.31  4909.7 1602.50  4939.9 1603.59  5003.6 1603.44  5025.5 1599.00
  5026.0 1598.50  5030.9 1599.00  5035.8 1602.00  5042.5 1599.02  5050.1 1603.74
  5056.7 1601.07  5064.3 1603.89  5262.7 1603.85  5397.5 1602.48  5418.3 1604.01
  5453.4 1609.79  5467.7 1613.58  5481.9 1613.17  5496.2 1616.31  5503.8 1619.03
  5510.4 1619.14  5518.0 1620.61  5524.6 1619.16  5528.4 1621.24  5531.8 1621.24
#Mann=3,-1,0
  4343.7    0.05       0  5025.5    0.05       0  5030.9    0.05       0
Bank Sta=5025.5,5030.9
Exp/Cntr=0.3,0.1

Type RM Length L Ch R = 1,9041,612,612,612
BEGIN DESCRIPTION:
Deadman 16 9.0
END DESCRIPTION:
XS GIS Cut Line= 3
      1590722.67      6897693.92      1591455.00      6897538.00
      1591805.02      6897037.98
#Sta/Elev= 30
  4245.1 1613.76  4431.5 1613.10  4574.7 1610.11  4632.3 1607.50  4830.6 1602.04
  4881.4 1601.82  4952.9 1603.01  4969.1 1602.06  4974.2 1599.00  4980.9 1598.80
  4981.3 1598.30  4986.3 1598.80  4991.3 1600.32  5001.3 1600.05  5016.1 1601.65
  5051.8 1602.32  5209.6 1601.56  5296.0 1602.37  5346.5 1601.45  5382.3 1602.99
  5453.8 1601.19  5482.1 1603.15  5495.6 1605.93  5518.7 1611.95  5525.3 1614.74
  5540.1 1618.81  5554.9 1622.06  5561.0 1621.98  5575.8 1625.20  5604.2 1627.38
#Mann=3,-1,0
  4245.1    0.05       0  4980.9    0.05       0  4986.3    0.05       0
Bank Sta=4980.9,4986.3
Exp/Cntr=0.3,0.1

Type RM Length L Ch R = 1,8429,0,0,0
BEGIN DESCRIPTION:
Deadman 16 6.0
END DESCRIPTION:
XS GIS Cut Line= 3
      1591154.98      6898188.01      1591654.46      6898072.79
      1592338.62      6897433.59
#Sta/Elev= 30
  4487.4 1611.33  4602.0 1610.35  4661.9 1607.58  4692.7 1607.25  4744.0 1604.42
  4868.9 1601.54  4887.7 1600.64  4909.0 1597.54  4909.4 1597.04  4914.5 1597.54
  4939.0 1598.28  4959.6 1600.39  4999.5 1601.01  5003.8 1601.01  5017.8 1597.82
  5032.0 1600.69  5088.6 1600.90  5123.9 1600.12  5308.0 1601.59  5399.8 1599.38
  5435.5 1600.75  5718.3 1605.06  5739.7 1605.87  5789.2 1609.96  5860.0 1617.37
  5866.8 1618.76  5874.2 1618.83  5902.5 1621.77  5923.5 1624.59  5936.3 1625.08
#Mann=3,-1,0
  4487.4    0.05       0  4909.0    0.05       0  4914.5    0.05       0
Bank Sta=4909,4914.5
Exp/Cntr=0.3,0.1

Chan Stop Cuts=-1