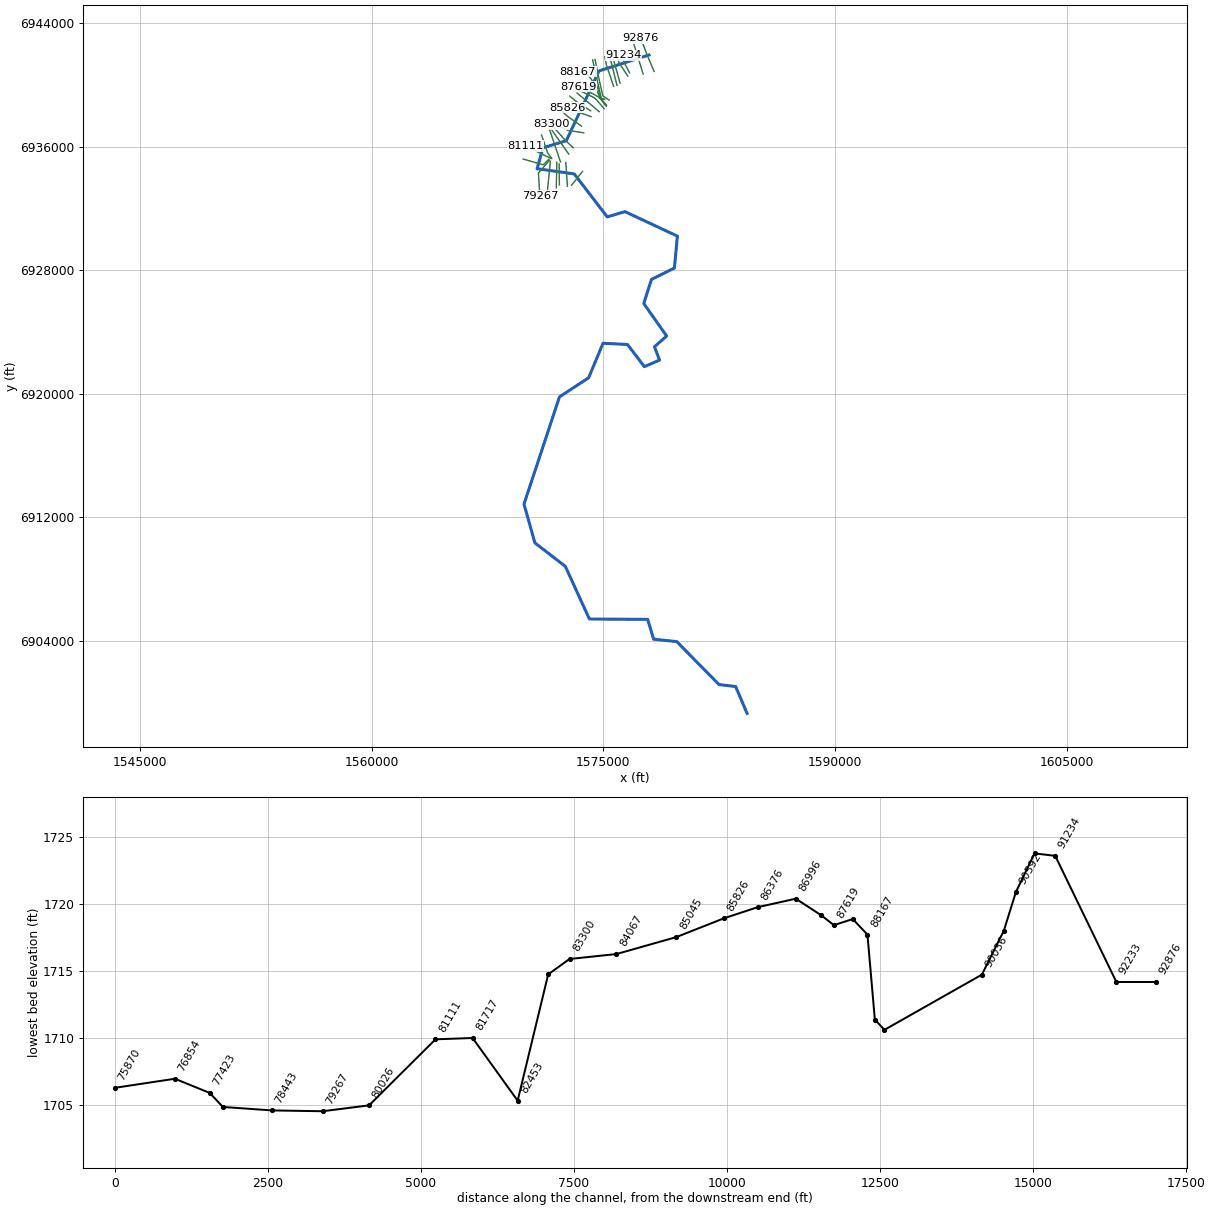
--- Deadman 17.prj (project) ---

Proj Title=Deadman 17 Base Level Engineering
Current Plan=p01
Default Exp/Contr=0.3,0.1
English Units
Geom File=g01
Flow File=f01
Plan File=p01
BEGIN DESCRIPTION:
Deadman 17
END DESCRIPTION:

--- Deadman 17.p01 (plan) ---

Plan Title=Multiple Run
Short Identifier=Multiple
Geom File=g01
Flow File=f01
Subcritical Flow
K Sum by GR= 0
Std Step Tol= 0.01
Critical Tol= 0.01
Num of Std Step Trials= 20
Max Error Tol= 0.3
Flow Tol Ratio= 0.001
Split Flow NTrial= 30
Split Flow Tol= 0.02
Split Flow Ratio= 0.02
Log Output Level= 0
Friction Slope Method= 1
Unsteady Friction Slope Method= 2
Unsteady Bridges Friction Slope Method= 1
Parabolic Critical Depth
Global Vel Dist=  1 , 1 , 1
Global Log Level= 0
CheckData=True
Encroach Param= -1, 0, 0, 0
BEGIN DESCRIPTION:
Multiple Run
END DESCRIPTION:

--- Deadman 17.f01 (steady flow) ---

Flow Title=Multiple
Number of Profiles=7
Profile Names=10-year,25-year,50-year,1pct_min,100-year,1pct_plu,500-year
River Rch & RM= Deadman 17,Reach-1,92876
     117     148     171      98     196     391     260
River Rch & RM= Deadman 17,Reach-1,88445
     292     395     477     286     571    1139     829
River Rch & RM= Deadman 17,Reach-1,85045
     311     420     507     303     605    1207     874
River Rch & RM= Deadman 17,Reach-1,79267
     408     557     676     406     811    1618    1184
River Rch & RM= Deadman 17,Reach-1,74077
     434     593     721     434     867    1729    1270
River Rch & RM= Deadman 17,Reach-1,65695
     537     741     905     548    1093    2181    1616
River Rch & RM= Deadman 17,Reach-1,61073
     596     827    1016     618    1233    2460    1841
River Rch & RM= Deadman 17,Reach-1,58439
     881    1245    1549     953    1902    3794    2907
River Rch & RM= Deadman 17,Reach-1,46106
     883    1246    1548     951    1898    3786    2893
River Rch & RM= Deadman 17,Reach-1,42358
     856    1202    1490     913    1821    3633    2760
River Rch & RM= Deadman 17,Reach-1,39073
     929    1308    1623     996    1987    3964    3018
River Rch & RM= Deadman 17,Reach-1,36940
     882    1234    1523     930    1855    3702    2791
River Rch & RM= Deadman 17,Reach-1,19946
    1044    1478    1841    1133    2261    4511    3459
River Rch & RM= Deadman 17,Reach-1,14108
    1077    1527    1903    1173    2340    4670    3589
River Rch & RM= Deadman 17,Reach-1,12802
    1213    1733    2171    1345    2684    5356    4159
River Rch & RM= Deadman 17,Reach-1,7370
    1245    1781    2234    1385    2764    5515    4291
River Rch & RM= Deadman 17,Reach-1,268
    1237    1767    2215    1372    2738    5463    4242
Boundary for River Rch & Prof#=Deadman 17,Reach-1,1
Up Type=0
Dn Type=3
Dn Slope=0.005
Boundary for River Rch & Prof#=Deadman 17,Reach-1,2
Up Type=0
Dn Type=3
Dn Slope=0.005
Boundary for River Rch & Prof#=Deadman 17,Reach-1,3
Up Type=0
Dn Type=3
Dn Slope=0.005
Boundary for River Rch & Prof#=Deadman 17,Reach-1,4
Up Type=0
Dn Type=3
Dn Slope=0.005
Boundary for River Rch & Prof#=Deadman 17,Reach-1,5
Up Type=0
Dn Type=3
Dn Slope=0.005
Boundary for River Rch & Prof#=Deadman 17,Reach-1,6
Up Type=0
Dn Type=3
Dn Slope=0.005
Boundary for River Rch & Prof#=Deadman 17,Reach-1,7
Up Type=0
Dn Type=3
Dn Slope=0.005

--- Deadman 17.g01 (geometry) ---

Geom Title=Existing Conditions

River Reach=Deadman 17,Reach-1
Reach XY= 30
      1577955.00      6941938.00      1574717.92      6940901.50
      1572597.15      6936381.81      1571088.32      6935921.36
      1570704.49      6934567.79      1573111.21      6934230.24
      1575248.06      6931446.83      1576394.52      6931787.07
      1579791.78      6930201.67      1579597.49      6928134.83
      1578115.95      6927398.38      1577612.77      6925834.59
      1579096.03      6923731.30      1578306.56      6923031.91
      1578638.82      6922171.30      1577651.68      6921746.04
      1576557.55      6923183.01      1574977.36      6923261.70
      1574041.60      6921024.67      1572155.00      6919788.00
      1569856.50      6912843.82      1570562.76      6910331.83
      1572535.77      6908808.57      1574091.64      6905401.41
      1577865.32      6905377.17      1578252.03      6904093.52
      1579753.78      6903934.63      1582487.83      6901154.11
      1583564.70      6901027.23      1584305.00      6899288.00

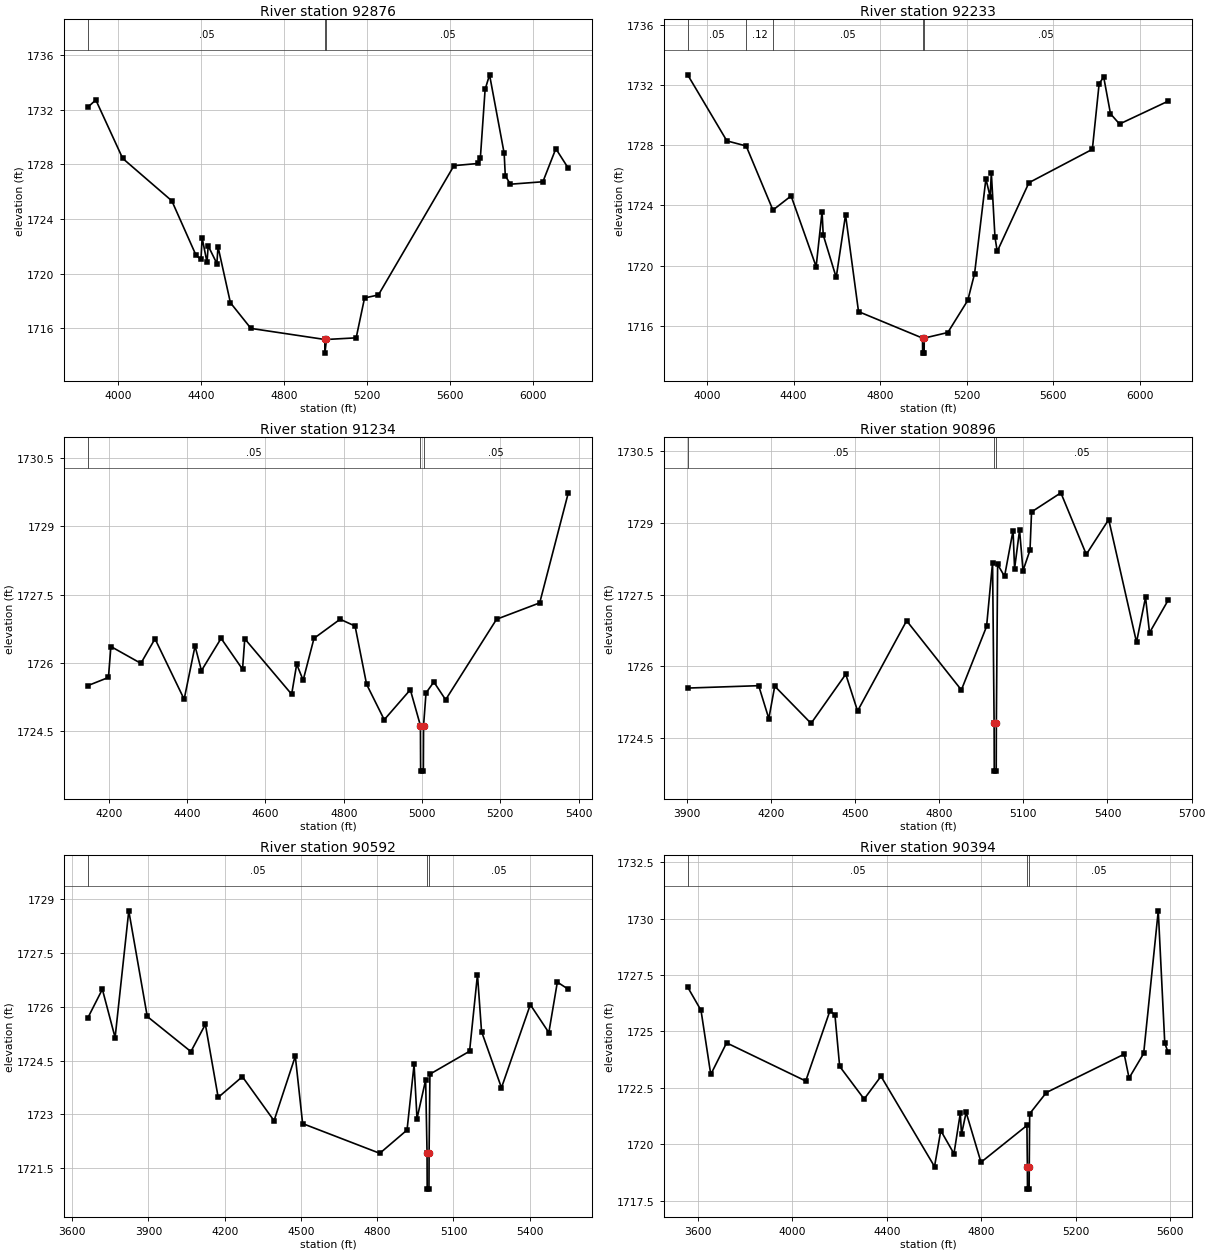
Type RM Length L Ch R = 1,92876,643,643,643
BEGIN DESCRIPTION:
Mapping XS c2063c78
END DESCRIPTION:
XS GIS Cut Line= 3
      1578284.03      6940865.15      1577837.92      6941921.24
      1577419.69      6943012.28
#Sta/Elev= 30
  3854.2 1732.19  3892.8 1732.72  4022.2 1728.44  4259.0 1725.33  4375.7 1721.34
  4399.4 1721.05  4404.9 1722.62  4428.6 1720.82  4434.0 1722.04  4476.0 1720.74
  4481.4 1721.98  4541.2 1717.87  4639.9 1715.99  4996.0 1715.18  4996.5 1714.18
  5004.0 1715.18  5147.1 1715.30  5187.5 1718.22  5254.2 1718.44  5618.3 1727.91
  5736.1 1728.07  5745.3 1728.45  5768.3 1733.49  5789.7 1734.56  5860.1 1728.81
  5865.5 1727.17  5890.1 1726.55  6046.7 1726.73  6109.0 1729.15  6169.1 1727.72
#Mann=3,-1,0
  3854.2    0.05       0  4996.0    0.05       0  5004.0    0.05       0
Bank Sta=4996,5004
Exp/Cntr=0.3,0.1

Type RM Length L Ch R = 1,92233,999,999,999
BEGIN DESCRIPTION:
Mapping XS b3a56b8c
END DESCRIPTION:
XS GIS Cut Line= 2
      1577573.91      6940701.32      1576918.42      6942822.55
#Sta/Elev= 30
  3910.8 1732.68  4091.9 1728.29  4181.2 1727.95  4304.8 1723.69  4388.8 1724.63
  4504.5 1719.93  4531.9 1723.59  4537.1 1722.04  4597.2 1719.21  4640.3 1723.37
  4700.3 1716.94  4996.0 1715.18  4996.5 1714.18  5003.5 1714.18  5004.0 1715.18
  5112.9 1715.55  5205.2 1717.69  5236.6 1719.47  5288.9 1725.77  5308.7 1724.56
  5313.9 1726.18  5330.8 1721.90  5341.2 1720.94  5487.8 1725.51  5780.8 1727.73
  5812.2 1732.10  5833.2 1732.53  5864.6 1730.09  5906.4 1729.41  6131.0 1730.93
#Mann=5,-1,0
  3910.8    0.05       0  4181.2    0.12       0  4304.8    0.05       0
  4996.0    0.05       0  5004.0    0.05       0
Bank Sta=4996,5004
Exp/Cntr=0.3,0.1

Type RM Length L Ch R = 1,91234,338,338,338
BEGIN DESCRIPTION:
Mapping XS f2c79a71
END DESCRIPTION:
XS GIS Cut Line= 3
      1576693.98      6940775.63      1576317.55      6941501.20
      1576293.24      6941910.97
#Sta/Elev= 30
  4146.0 1725.50  4198.7 1725.68  4205.0 1726.36  4281.6 1725.99  4317.7 1726.53
  4392.2 1725.20  4420.0 1726.37  4436.4 1725.83  4486.6 1726.54  4541.4 1725.86
  4547.1 1726.53  4666.9 1725.31  4679.8 1725.97  4696.3 1725.62  4724.0 1726.54
  4790.8 1726.96  4829.0 1726.81  4858.4 1725.53  4903.5 1724.75  4970.2 1725.41
  4996.0 1724.62  4996.5 1723.62  5003.5 1723.62  5004.0 1724.62  5010.3 1725.34
  5030.3 1725.58  5060.4 1725.19  5190.6 1726.96  5300.8 1727.32  5373.9 1729.74
#Mann=3,-1,0
  4146.0    0.05       0  4996.0    0.05       0  5004.0    0.05       0
Bank Sta=4996,5004
Exp/Cntr=0.3,0.1

Type RM Length L Ch R = 1,90896,304,304,304
BEGIN DESCRIPTION:
Mapping XS 5e9df54f
END DESCRIPTION:
XS GIS Cut Line= 3
      1576580.01      6940562.99      1576022.41      6941410.92
      1575775.99      6942063.39
#Sta/Elev= 30
  3903.9 1725.54  4157.0 1725.59  4193.1 1724.90  4214.2 1725.58  4343.7 1724.80
  4467.3 1725.83  4509.4 1725.06  4684.2 1726.95  4879.3 1725.50  4969.1 1726.83
  4990.5 1728.17  4996.0 1724.80  4996.5 1723.80  5003.5 1723.80  5004.0 1724.80
  5008.5 1728.13  5033.2 1727.88  5063.5 1728.84  5068.9 1728.04  5086.7 1728.85
  5099.0 1728.00  5123.9 1728.43  5129.4 1729.23  5233.9 1729.63  5324.5 1728.34
  5404.4 1729.07  5503.5 1726.50  5535.6 1727.44  5549.9 1726.70  5616.2 1727.38
#Mann=3,-1,0
  3903.9    0.05       0  4996.0    0.05       0  5004.0    0.05       0
Bank Sta=4996,5004
Exp/Cntr=0.3,0.1

Type RM Length L Ch R = 1,90592,198,198,198
BEGIN DESCRIPTION:
Mapping XS f53bca3d
END DESCRIPTION:
XS GIS Cut Line= 2
      1576080.00      6940112.98      1575567.54      6941931.77
#Sta/Elev= 30
  3661.9 1725.69  3719.1 1726.49  3769.2 1725.14  3823.0 1728.68  3895.7 1725.73
  4067.3 1724.75  4124.2 1725.51  4174.6 1723.47  4269.7 1724.05  4394.3 1722.82
  4477.9 1724.62  4506.7 1722.74  4810.1 1721.91  4917.3 1722.56  4945.0 1724.39
  4956.5 1722.88  4990.5 1723.96  4996.0 1721.91  4996.5 1720.91  5003.5 1720.91
  5004.0 1721.91  5007.3 1724.12  5163.2 1724.76  5194.3 1726.90  5210.3 1725.31
  5288.7 1723.74  5402.1 1726.06  5474.9 1725.28  5508.4 1726.69  5551.5 1726.49
#Mann=3,-1,0
  3661.9    0.05       0  4996.0    0.05       0  5004.0    0.05       0
Bank Sta=4996,5004
Exp/Cntr=0.3,0.1

Type RM Length L Ch R = 1,90394,358,358,358
BEGIN DESCRIPTION:
Mapping XS 76d17965
END DESCRIPTION:
XS GIS Cut Line= 2
      1575879.99      6939963.05      1575387.00      6941938.67
#Sta/Elev= 30
  3556.4 1726.96  3613.0 1725.93  3654.3 1723.09  3721.4 1724.49  4056.7 1722.80
  4159.3 1725.91  4180.5 1725.73  4200.5 1723.45  4304.3 1722.00  4375.7 1723.01
  4602.5 1719.01  4629.2 1720.60  4684.9 1719.58  4711.8 1721.37  4716.9 1720.44
  4736.5 1721.41  4799.5 1719.20  4994.1 1720.83  4996.0 1719.01  4996.5 1718.01
  5003.5 1718.01  5004.0 1719.01  5005.8 1721.35  5076.6 1722.29  5406.4 1723.99
  5427.0 1722.93  5488.8 1724.02  5550.7 1730.34  5578.3 1724.47  5592.6 1724.07
#Mann=3,-1,0
  3556.4    0.05       0  4996.0    0.03       0  5004.0    0.05       0
Bank Sta=4996,5004
Exp/Cntr=0.3,0.1

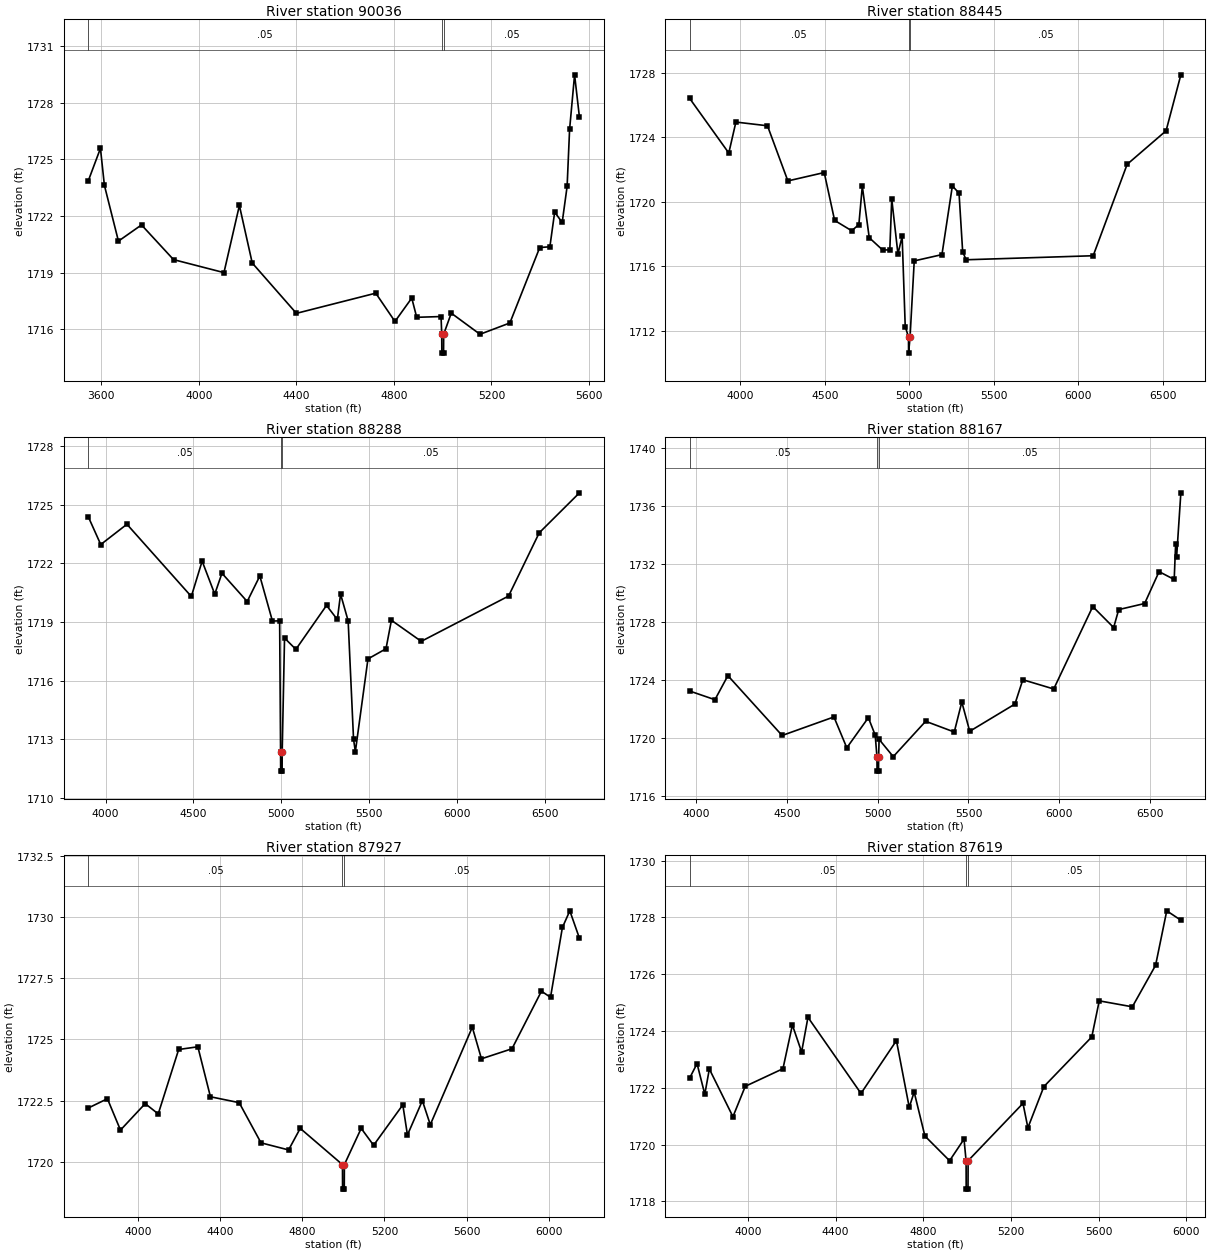
Type RM Length L Ch R = 1,90036,1591,1591,1591
BEGIN DESCRIPTION:
Mapping XS a5af79b1
END DESCRIPTION:
XS GIS Cut Line= 3
      1575661.29      6939900.53      1575196.02      6941282.45
      1575084.90      6941827.60
#Sta/Elev= 30
  3546.3 1723.86  3596.4 1725.59  3612.6 1723.63  3670.2 1720.67  3764.8 1721.53
  3896.1 1719.69  4102.9 1719.00  4166.2 1722.56  4218.9 1719.51  4400.0 1716.84
  4725.4 1717.91  4804.2 1716.41  4873.1 1717.65  4893.4 1716.63  4993.2 1716.67
  4996.0 1715.73  4996.5 1714.73  5003.5 1714.73  5004.0 1715.73  5035.1 1716.85
  5153.0 1715.73  5275.5 1716.33  5397.9 1720.33  5439.5 1720.37  5459.2 1722.21
  5490.0 1721.66  5510.2 1723.57  5520.4 1726.60  5540.8 1729.49  5560.8 1727.24
#Mann=3,-1,0
  3546.3    0.05       0  4996.0    0.05       0  5004.0    0.05       0
Bank Sta=4996,5004
Exp/Cntr=0.3,0.1

Type RM Length L Ch R = 1,88445,157,157,157
BEGIN DESCRIPTION:
Mapping XS 47a7d085
END DESCRIPTION:
XS GIS Cut Line= 4
      1575380.01      6939012.99      1574962.57      6939288.03
      1574727.26      6940325.37      1574455.65      6941643.68
#Sta/Elev= 30
  3699.0 1726.40  3930.9 1723.01  3973.0 1724.93  4160.1 1724.70  4280.9 1721.28
  4496.2 1721.80  4557.8 1718.83  4658.9 1718.19  4701.3 1718.57  4721.8 1720.95
  4762.8 1717.76  4841.6 1717.00  4884.7 1717.00  4896.1 1720.16  4932.9 1716.75
  4957.7 1717.84  4976.0 1712.25  4995.4 1711.60  4995.9 1710.60  5004.6 1711.60
  5029.4 1716.32  5193.5 1716.71  5255.2 1720.97  5294.7 1720.52  5316.3 1716.88
  5336.8 1716.39  6089.3 1716.64  6290.5 1722.31  6521.1 1724.39  6608.6 1727.86
#Mann=3,-1,0
  3699.0    0.05       0  4995.4    0.03       0  5004.6    0.05       0
Bank Sta=4995.4,5004.6
Exp/Cntr=0.3,0.1

Type RM Length L Ch R = 1,88288,121,121,121
BEGIN DESCRIPTION:
Mapping XS d1f1ff35
END DESCRIPTION:
XS GIS Cut Line= 3
      1575085.23      6939065.98      1574866.46      6939102.44
      1574303.05      6941611.26
#Sta/Elev= 30
  3901.7 1724.40  3972.9 1722.97  4121.7 1724.01  4487.9 1720.31  4549.4 1722.12
  4621.1 1720.43  4662.1 1721.50  4805.6 1720.05  4877.4 1721.36  4949.1 1719.05
  4990.1 1719.06  4995.4 1712.36  4995.9 1711.36  5004.1 1711.36  5004.6 1712.36
  5017.9 1718.18  5082.4 1717.60  5256.6 1719.85  5318.1 1719.13  5336.5 1720.43
  5379.6 1719.06  5410.3 1712.99  5420.6 1712.36  5492.3 1717.11  5594.8 1717.63
  5625.6 1719.09  5795.3 1718.01  6291.7 1720.33  6466.0 1723.57  6694.8 1725.62
#Mann=3,-1,0
  3901.7    0.05       0  4995.4    0.03       0  5004.6    0.05       0
Bank Sta=4995.4,5004.6
Exp/Cntr=0.3,0.1

Type RM Length L Ch R = 1,88167,240,240,240
BEGIN DESCRIPTION:
Mapping XS 0ac25ae8
END DESCRIPTION:
XS GIS Cut Line= 5
      1575064.43      6939062.17      1574855.71      6939092.87
      1574622.50      6939829.35      1573978.07      6940670.16
      1573339.87      6940860.40
#Sta/Elev= 30
  3962.4 1723.25  4101.9 1722.65  4173.4 1724.31  4472.4 1720.18  4758.2 1721.46
  4829.1 1719.33  4947.9 1721.41  4985.6 1720.21  4995.4 1718.72  4995.9 1717.72
  5004.1 1717.72  5004.6 1718.72  5007.2 1719.91  5085.3 1718.72  5263.9 1721.16
  5421.7 1720.42  5463.3 1722.49  5506.9 1720.47  5756.2 1722.35  5799.7 1724.03
  5970.1 1723.39  6185.4 1729.08  6300.6 1727.63  6328.5 1728.87  6471.5 1729.29
  6551.1 1731.49  6634.5 1730.95  6642.5 1733.43  6647.7 1732.49  6671.2 1736.93
#Mann=3,-1,0
  3962.4    0.05       0  4995.4    0.03       0  5004.6    0.05       0
Bank Sta=4995.4,5004.6
Exp/Cntr=0.3,0.1

Type RM Length L Ch R = 1,87927,308,308,308
BEGIN DESCRIPTION:
Mapping XS 1e41fddf
END DESCRIPTION:
XS GIS Cut Line= 5
      1575202.43      6938683.55      1574859.83      6939072.61
      1574833.31      6939082.55      1574564.87      6939622.76
      1573461.26      6940196.11
#Sta/Elev= 30
  3756.5 1722.20  3850.0 1722.58  3913.6 1721.30  4034.1 1722.38  4097.6 1721.96
  4197.2 1724.59  4290.7 1724.70  4352.0 1722.66  4492.0 1722.42  4598.4 1720.78
  4732.8 1720.49  4789.5 1721.37  4995.4 1719.89  4995.9 1718.89  5004.1 1718.89
  5004.6 1719.89  5086.6 1721.37  5147.1 1720.68  5289.4 1722.33  5312.0 1721.10
  5384.7 1722.50  5423.3 1721.52  5628.0 1725.50  5672.6 1724.21  5821.4 1724.62
  5964.9 1726.97  6009.1 1726.72  6067.0 1729.57  6103.2 1730.25  6150.1 1729.13
#Mann=3,-1,0
  3756.5    0.05       0  4995.4    0.05       0  5004.6    0.05       0
Bank Sta=4995.4,5004.6
Exp/Cntr=0.3,0.1

Type RM Length L Ch R = 1,87619,203,203,203
BEGIN DESCRIPTION:
Mapping XS fdd49578
END DESCRIPTION:
XS GIS Cut Line= 5
      1575182.42      6938608.47      1574846.57      6939039.47
      1574690.80      6939208.49      1574293.10      6939433.86
      1573391.69      6939881.25
#Sta/Elev= 30
  3734.9 1722.34  3768.7 1722.85  3804.0 1721.77  3824.8 1722.66  3932.4 1720.98
  3988.5 1722.05  4160.4 1722.67  4203.4 1724.21  4245.5 1723.26  4274.4 1724.48
  4516.2 1721.80  4677.8 1723.66  4736.2 1721.31  4758.6 1721.85  4807.6 1720.30
  4920.1 1719.43  4985.9 1720.19  4995.4 1719.43  4995.9 1718.43  5004.1 1718.43
  5004.6 1719.43  5254.8 1721.45  5277.2 1720.59  5350.0 1722.04  5568.5 1723.79
  5602.5 1725.06  5753.4 1724.85  5859.3 1726.31  5910.3 1728.23  5974.6 1727.90
#Mann=3,-1,0
  3734.9    0.05       0  4995.4    0.03       0  5004.6    0.05       0
Bank Sta=4995.4,5004.6
Exp/Cntr=0.3,0.1

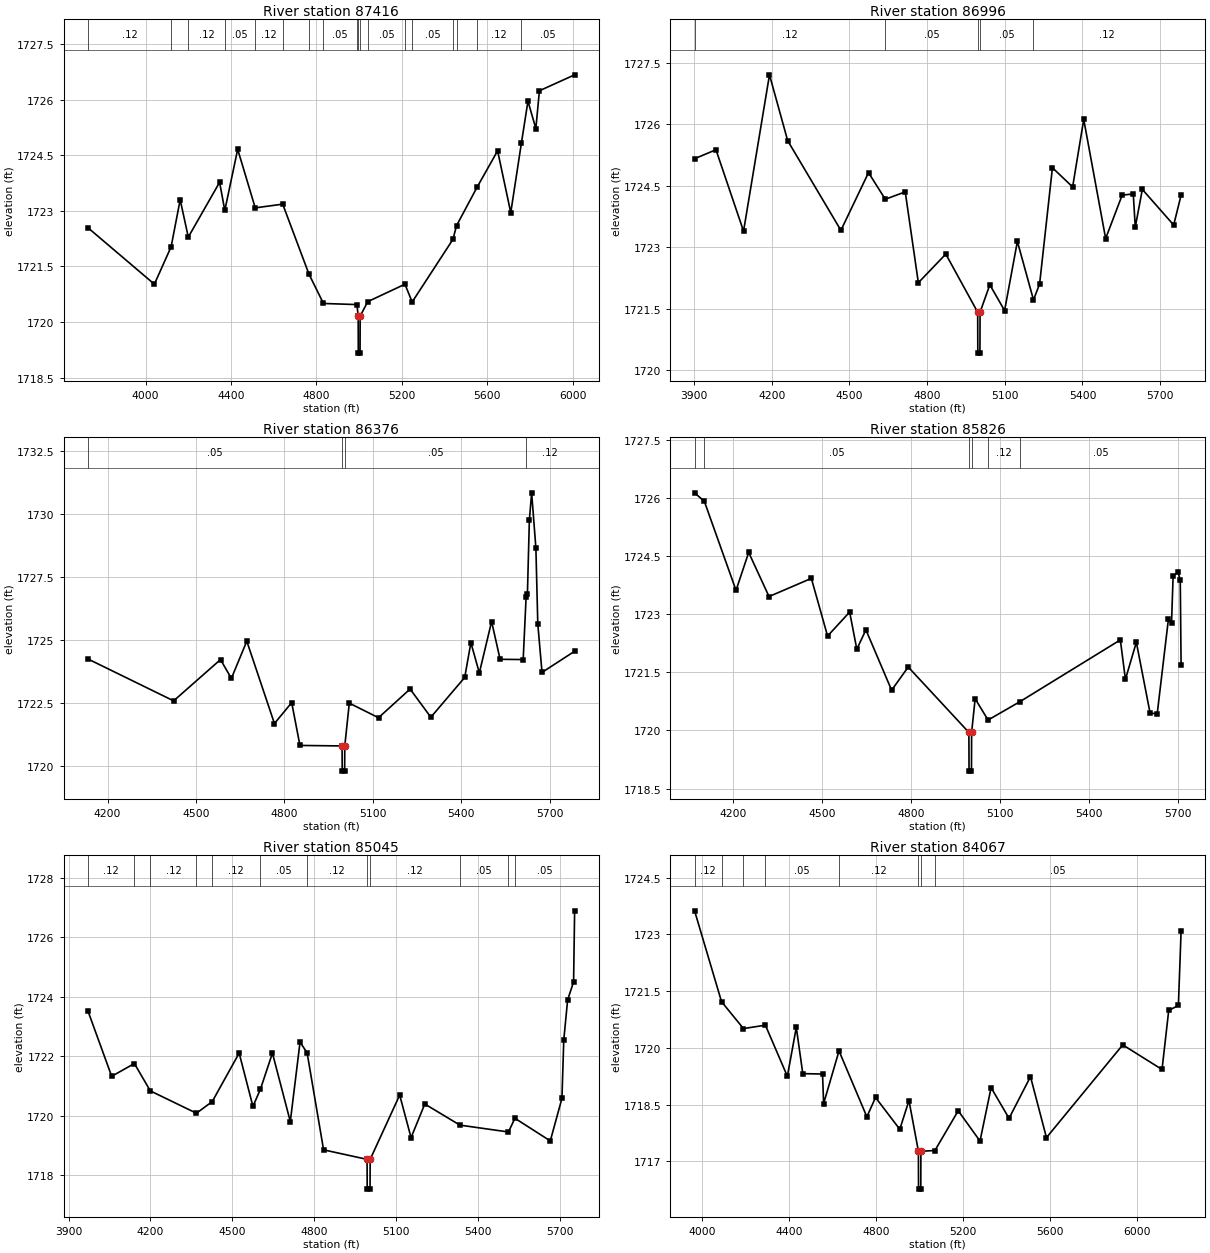
Type RM Length L Ch R = 1,87416,420,420,420
BEGIN DESCRIPTION:
Mapping XS 98a76640
END DESCRIPTION:
XS GIS Cut Line= 4
      1575042.27      6938458.32      1574544.98      6939042.78
      1574405.79      6939162.09      1573219.62      6939755.18
#Sta/Elev= 30
  3731.4 1722.54  4041.5 1721.02  4119.9 1722.03  4162.3 1723.30  4200.2 1722.29
  4346.8 1723.77  4371.1 1723.01  4431.4 1724.66  4513.5 1723.08  4642.1 1723.18
  4765.1 1721.29  4832.8 1720.50  4989.6 1720.47  4995.4 1720.16  4995.9 1719.16
  5004.1 1719.16  5004.6 1720.16  5040.4 1720.55  5214.2 1721.02  5248.0 1720.54
  5438.8 1722.23  5455.6 1722.60  5551.1 1723.63  5647.9 1724.62  5709.4 1722.95
  5759.5 1724.84  5789.9 1725.96  5826.8 1725.22  5843.5 1726.24  6008.3 1726.67
#Mann=18,-1,0
  3731.4    0.12       0  4119.9    0.05       0  4200.2    0.12       0
  4371.1    0.05       0  4513.5    0.12       0  4642.1    0.05       0
  4765.1    0.12       0  4832.8    0.05       0  4989.6    0.12       0
  4995.4    0.07       0  5004.6    0.12       0  5040.4    0.05       0
  5214.2    0.12       0  5248.0    0.05       0  5438.8    0.12       0
  5455.6    0.05       0  5551.1    0.12       0  5759.5    0.05       0
Bank Sta=4995.4,5004.6
Exp/Cntr=0.3,0.1

Type RM Length L Ch R = 1,86996,620,620,620
BEGIN DESCRIPTION:
Mapping XS 46c74852
END DESCRIPTION:
XS GIS Cut Line= 2
      1574726.96      6938263.10      1573290.10      6939473.14
#Sta/Elev= 30
  3902.3 1725.16  3984.8 1725.38  4091.4 1723.39  4191.5 1727.21  4261.8 1725.60
  4467.3 1723.41  4573.9 1724.82  4638.7 1724.17  4715.7 1724.35  4766.3 1722.13
  4872.3 1722.83  4995.4 1721.41  4995.9 1720.41  5004.1 1720.41  5004.6 1721.41
  5042.3 1722.08  5099.3 1721.45  5148.7 1723.14  5210.9 1721.71  5234.5 1722.10
  5284.0 1724.94  5362.0 1724.47  5404.9 1726.12  5489.5 1723.21  5553.2 1724.27
  5596.1 1724.30  5603.9 1723.49  5631.2 1724.41  5752.2 1723.54  5780.8 1724.27
#Mann=5,-1,0
  3902.3    0.12       0  4638.7    0.05       0  4995.4    0.05       0
  5004.6    0.05       0  5210.9    0.12       0
Bank Sta=4995.4,5004.6
Exp/Cntr=0.3,0.1

Type RM Length L Ch R = 1,86376,550,550,550
BEGIN DESCRIPTION:
Mapping XS e0bfebfe
END DESCRIPTION:
XS GIS Cut Line= 3
      1574175.15      6938320.66      1573432.13      6938772.03
      1572825.81      6939264.02
#Sta/Elev= 30
  4134.0 1724.23  4424.1 1722.57  4583.1 1724.21  4619.9 1723.46  4672.2 1724.94
  4766.0 1721.67  4824.5 1722.50  4852.5 1720.80  4995.4 1720.78  4995.9 1719.78
  5004.1 1719.78  5004.6 1720.78  5019.9 1722.48  5119.0 1721.90  5226.1 1723.04
  5296.5 1721.92  5411.4 1723.50  5432.3 1724.88  5461.0 1723.68  5502.6 1725.72
  5531.4 1724.22  5609.7 1724.21  5619.6 1726.68  5624.1 1726.83  5630.7 1729.75
  5638.4 1730.83  5652.8 1728.64  5659.3 1725.62  5673.6 1723.70  5784.2 1724.54
#Mann=4,-1,0
  4134.0    0.05       0  4995.4    0.05       0  5004.6    0.05       0
  5619.6    0.12       0
Bank Sta=4995.4,5004.6
Exp/Cntr=0.3,0.1

Type RM Length L Ch R = 1,85826,781,781,781
BEGIN DESCRIPTION:
Mapping XS 391580c2
END DESCRIPTION:
XS GIS Cut Line= 3
      1574196.41      6937937.77      1573380.61      6938233.06
      1572665.30      6938523.18
#Sta/Elev= 30
  4071.0 1726.14  4103.9 1725.92  4210.7 1723.62  4253.3 1724.60  4321.9 1723.46
  4464.5 1723.93  4519.2 1722.44  4593.6 1723.06  4617.7 1722.10  4648.4 1722.60
  4735.0 1721.04  4790.9 1721.64  4995.4 1719.95  4995.9 1718.95  5004.1 1718.95
  5004.6 1719.95  5016.5 1720.82  5060.0 1720.27  5166.4 1720.74  5505.8 1722.34
  5522.9 1721.32  5559.7 1722.28  5606.0 1720.45  5630.0 1720.43  5667.7 1722.87
  5678.2 1722.77  5683.6 1723.98  5700.0 1724.10  5707.7 1723.88  5710.5 1721.69
#Mann=6,-1,0
  4071.0    0.12       0  4103.9    0.05       0  4995.4    0.05       0
  5004.6    0.05       0  5060.0    0.12       0  5166.4    0.05       0
Bank Sta=4995.4,5004.6
Exp/Cntr=0.3,0.1

Type RM Length L Ch R = 1,85045,978,978,978
BEGIN DESCRIPTION:
Mapping XS 95468e67
END DESCRIPTION:
XS GIS Cut Line= 3
      1573575.80      6937327.14      1572709.92      6937932.75
      1572164.47      6938413.15
#Sta/Elev= 30
  3971.7 1723.51  4058.1 1721.33  4141.3 1721.76  4199.8 1720.84  4368.8 1720.09
  4426.6 1720.48  4525.4 1722.11  4575.9 1720.32  4603.1 1720.89  4647.4 1722.11
  4712.9 1719.81  4748.6 1722.48  4774.5 1722.12  4834.9 1718.86  4994.3 1718.54
  4994.8 1717.54  5005.2 1717.54  5005.7 1718.54  5113.9 1720.70  5155.6 1719.27
  5205.9 1720.40  5334.8 1719.69  5512.6 1719.46  5536.3 1719.92  5666.0 1719.16
  5708.7 1720.59  5715.4 1722.55  5729.6 1723.90  5751.4 1724.50  5755.2 1726.89
#Mann=12,-1,0
  3971.7    0.12       0  4141.3    0.05       0  4199.8    0.12       0
  4368.8    0.05       0  4426.6    0.12       0  4603.1    0.05       0
  4774.5    0.12       0  4994.3    0.07       0  5005.7    0.12       0
  5334.8    0.05       0  5512.6    0.12       0  5536.3    0.05       0
Bank Sta=4994.3,5005.7
Exp/Cntr=0.3,0.1

Type RM Length L Ch R = 1,84067,767,767,767
BEGIN DESCRIPTION:
Mapping XS 81fed95d
END DESCRIPTION:
XS GIS Cut Line= 3
      1573725.94      6936891.70      1572699.91      6937051.86
      1571623.85      6937572.37
#Sta/Elev= 30
  3966.6 1723.62  4090.4 1721.22  4191.1 1720.51  4291.7 1720.60  4392.6 1719.25
  4433.6 1720.54  4463.5 1719.32  4554.1 1719.31  4559.1 1718.53  4629.8 1719.92
  4757.6 1718.18  4797.5 1718.69  4908.8 1717.85  4951.0 1718.61  4994.3 1717.27
  4994.8 1716.27  5005.2 1716.27  5005.7 1717.27  5070.1 1717.29  5177.1 1718.34
  5277.1 1717.54  5328.1 1718.95  5410.4 1718.14  5508.9 1719.24  5582.2 1717.63
  5932.5 1720.08  6112.9 1719.43  6143.6 1720.99  6188.0 1721.12  6200.4 1723.08
#Mann=8,-1,0
  3966.6    0.12       0  4090.4    0.05       0  4191.1    0.12       0
  4291.7    0.05       0  4629.8    0.12       0  4994.3    0.07       0
  5005.7    0.12       0  5070.1    0.05       0
Bank Sta=4994.3,5005.7
Exp/Cntr=0.3,0.1

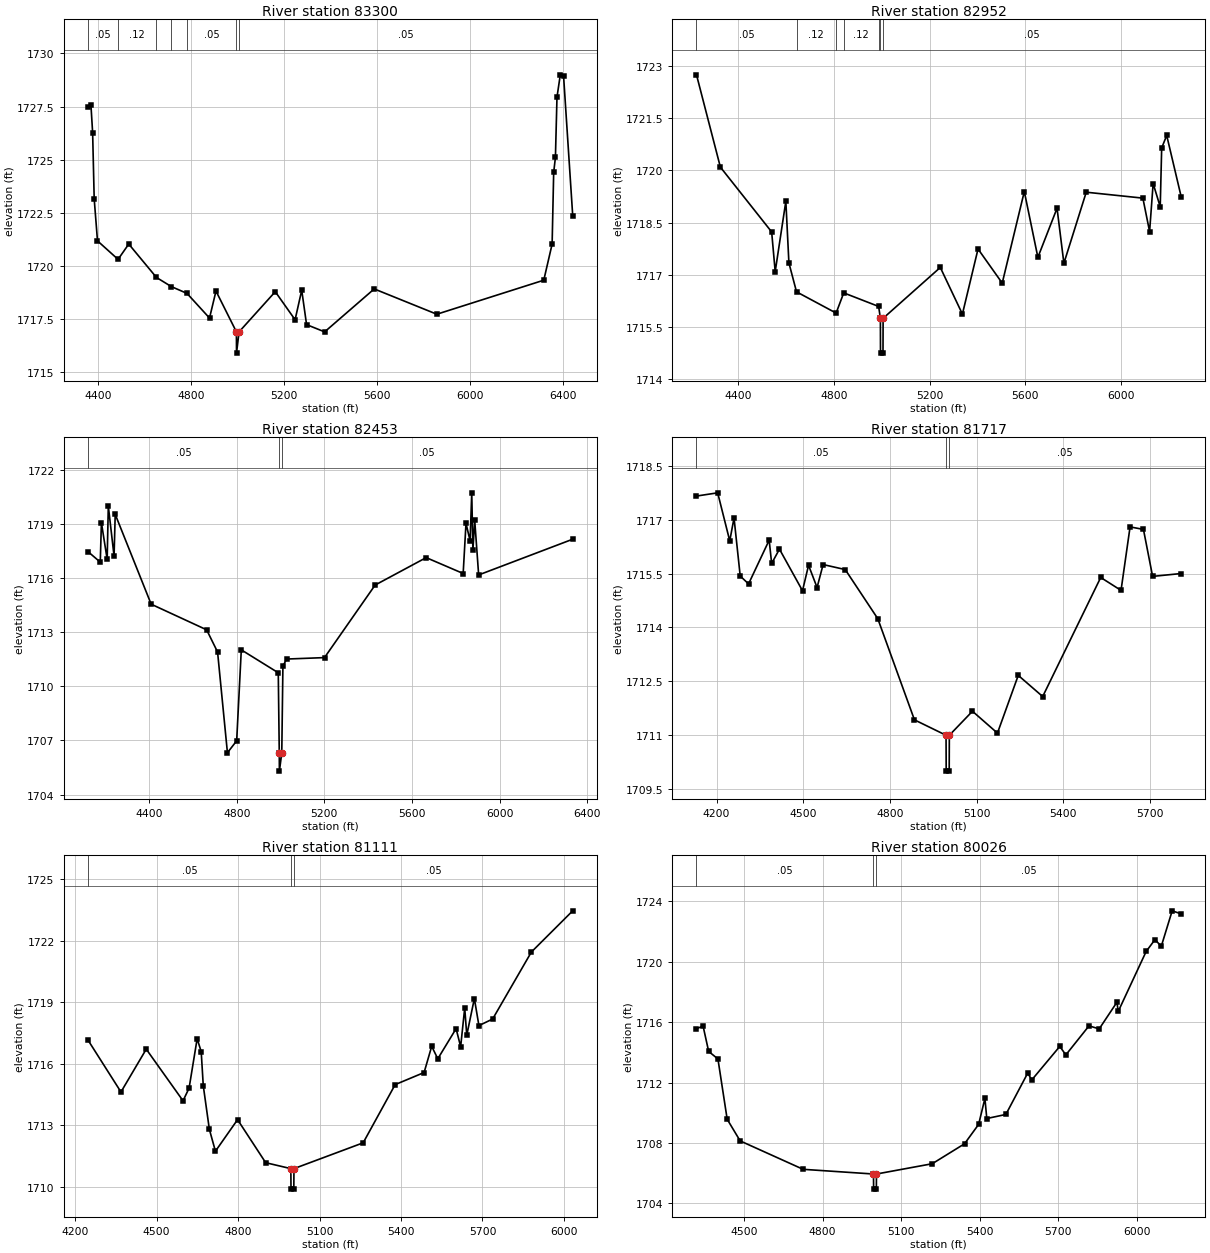
Type RM Length L Ch R = 1,83300,348,348,348
BEGIN DESCRIPTION:
Mapping XS f17e2abc
END DESCRIPTION:
XS GIS Cut Line= 3
      1573050.27      6935925.71      1572569.78      6936366.16
      1571613.84      6937432.21
#Sta/Elev= 30
  4356.4 1727.47  4368.8 1727.59  4376.2 1726.27  4382.9 1723.16  4397.1 1721.18
  4485.5 1720.31  4531.5 1721.03  4650.5 1719.46  4714.5 1719.03  4781.8 1718.71
  4878.7 1717.55  4906.5 1718.82  4994.3 1716.90  4994.8 1715.90  5005.7 1716.90
  5161.4 1718.79  5246.6 1717.47  5275.1 1718.86  5296.0 1717.24  5373.7 1716.90
  5586.8 1718.92  5855.9 1717.73  6315.7 1719.33  6351.6 1721.03  6358.3 1724.40
  6365.8 1725.11  6372.5 1727.94  6386.7 1728.99  6400.9 1728.92  6440.1 1722.37
#Mann=7,-1,0
  4356.4    0.05       0  4485.5    0.12       0  4650.5    0.05       0
  4714.5    0.12       0  4781.8    0.05       0  4994.3    0.05       0
  5005.7    0.05       0
Bank Sta=4994.3,5005.7
Exp/Cntr=0.3,0.1

Type RM Length L Ch R = 1,82952,499,499,499
BEGIN DESCRIPTION:
Mapping XS d6a25b5e
END DESCRIPTION:
XS GIS Cut Line= 2
      1572757.94      6935512.11      1571592.67      6937168.98
#Sta/Elev= 30
  4225.8 1722.74  4325.6 1720.09  4539.9 1718.23  4554.7 1717.09  4599.2 1719.11
  4612.0 1717.34  4643.8 1716.51  4809.3 1715.90  4841.1 1716.48  4987.0 1716.09
  4994.3 1715.75  4994.8 1714.75  5005.2 1714.75  5005.7 1715.75  5244.7 1717.21
  5337.1 1715.87  5402.4 1717.74  5503.5 1716.76  5595.8 1719.39  5652.5 1717.50
  5732.6 1718.91  5761.2 1717.33  5854.6 1719.37  6091.3 1719.20  6119.4 1718.24
  6134.2 1719.62  6163.8 1718.95  6169.9 1720.64  6190.9 1721.00  6251.4 1719.24
#Mann=7,-1,0
  4225.8    0.05       0  4643.8    0.12       0  4809.3    0.05       0
  4841.1    0.12       0  4987.0    0.05       0  4994.3    0.05       0
  5005.7    0.05       0
Bank Sta=4994.3,5005.7
Exp/Cntr=0.3,0.1

Type RM Length L Ch R = 1,82453,736,736,736
BEGIN DESCRIPTION:
Mapping XS b77919f8
END DESCRIPTION:
XS GIS Cut Line= 2
      1572219.41      6935004.81      1571513.69      6937101.95
#Sta/Elev= 30
  4121.2 1717.46  4177.1 1716.88  4182.3 1719.07  4208.6 1717.03  4213.8 1719.99
  4240.1 1717.21  4245.3 1719.53  4409.4 1714.55  4662.7 1713.13  4712.6 1711.90
  4757.6 1706.32  4799.8 1706.98  4820.9 1712.02  4989.7 1710.75  4994.3 1706.30
  4994.8 1705.30  5005.7 1706.30  5010.9 1711.11  5027.6 1711.51  5200.8 1711.59
  5431.9 1715.61  5665.0 1717.13  5833.8 1716.25  5846.7 1719.03  5865.5 1718.06
  5873.0 1720.72  5878.2 1717.54  5886.6 1719.19  5904.5 1716.17  6333.9 1718.15
#Mann=3,-1,0
  4121.2    0.05       0  4994.3    0.05       0  5005.7    0.05       0
Bank Sta=4994.3,5005.7
Exp/Cntr=0.3,0.1

Type RM Length L Ch R = 1,81717,606,606,606
BEGIN DESCRIPTION:
Mapping XS 11d614e6
END DESCRIPTION:
XS GIS Cut Line= 3
      1571653.86      6935224.98      1571388.58      6935595.37
      1570993.18      6936751.54
#Sta/Elev= 30
  4130.6 1717.66  4203.9 1717.75  4245.7 1716.41  4260.5 1717.05  4281.9 1715.43
  4310.8 1715.21  4382.1 1716.43  4390.7 1715.78  4417.7 1716.18  4497.5 1715.02
  4518.4 1715.73  4547.9 1715.11  4568.8 1715.75  4645.4 1715.61  4758.1 1714.24
  4884.9 1711.42  4994.3 1710.99  4994.8 1709.99  5005.2 1709.99  5005.7 1710.99
  5085.7 1711.66  5172.2 1711.05  5244.2 1712.66  5328.8 1712.07  5529.6 1715.39
  5599.9 1715.03  5631.2 1716.80  5677.5 1716.73  5709.2 1715.42  5808.1 1715.50
#Mann=3,-1,0
  4130.6    0.05       0  4994.3    0.05       0  5005.7    0.05       0
Bank Sta=4994.3,5005.7
Exp/Cntr=0.3,0.1

Type RM Length L Ch R = 1,81111,1085,1085,1085
BEGIN DESCRIPTION:
Mapping XS f04ea09b
END DESCRIPTION:
XS GIS Cut Line= 3
      1571573.80      6935255.01      1571303.49      6935375.15
      1569968.53      6936035.13
#Sta/Elev= 30
  4247.3 1717.16  4368.6 1714.63  4461.7 1716.72  4597.2 1714.20  4619.5 1714.82
  4649.2 1717.23  4664.1 1716.60  4671.7 1714.94  4694.1 1712.81  4716.5 1711.74
  4798.0 1713.28  4901.6 1711.18  4994.3 1710.89  4994.8 1709.89  5005.2 1709.89
  5005.7 1710.89  5260.6 1712.15  5378.4 1714.99  5485.0 1715.58  5513.0 1716.86
  5535.4 1716.25  5602.8 1717.72  5619.6 1716.84  5634.6 1718.73  5642.1 1717.40
  5670.1 1719.19  5686.9 1717.87  5737.4 1718.19  5880.1 1721.46  6032.3 1723.47
#Mann=3,-1,0
  4247.3    0.05       0  4994.3    0.05       0  5005.7    0.05       0
Bank Sta=4994.3,5005.7
Exp/Cntr=0.3,0.1

Type RM Length L Ch R = 1,80026,759,759,759
BEGIN DESCRIPTION:
Mapping XS 3476cc42
END DESCRIPTION:
XS GIS Cut Line= 3
      1571463.64      6935174.93      1571103.29      6934819.59
      1569811.94      6935189.97
#Sta/Elev= 30
  4318.9 1715.57  4344.1 1715.73  4365.3 1714.06  4400.7 1713.56  4436.0 1709.57
  4485.5 1708.14  4725.9 1706.26  4994.3 1705.95  4994.8 1704.95  5005.2 1704.95
  5005.7 1705.95  5218.5 1706.63  5341.7 1707.95  5395.4 1709.23  5419.5 1710.95
  5426.6 1709.62  5499.4 1709.89  5582.6 1712.62  5598.6 1712.18  5705.1 1714.39
  5728.3 1713.83  5816.7 1715.75  5855.6 1715.55  5923.1 1717.31  5928.3 1716.71
  6034.7 1720.67  6068.5 1721.46  6092.4 1721.01  6134.0 1723.36  6168.4 1723.16
#Mann=3,-1,0
  4318.9    0.05       0  4994.3    0.05       0  5005.7    0.05       0
Bank Sta=4994.3,5005.7
Exp/Cntr=0.3,0.1

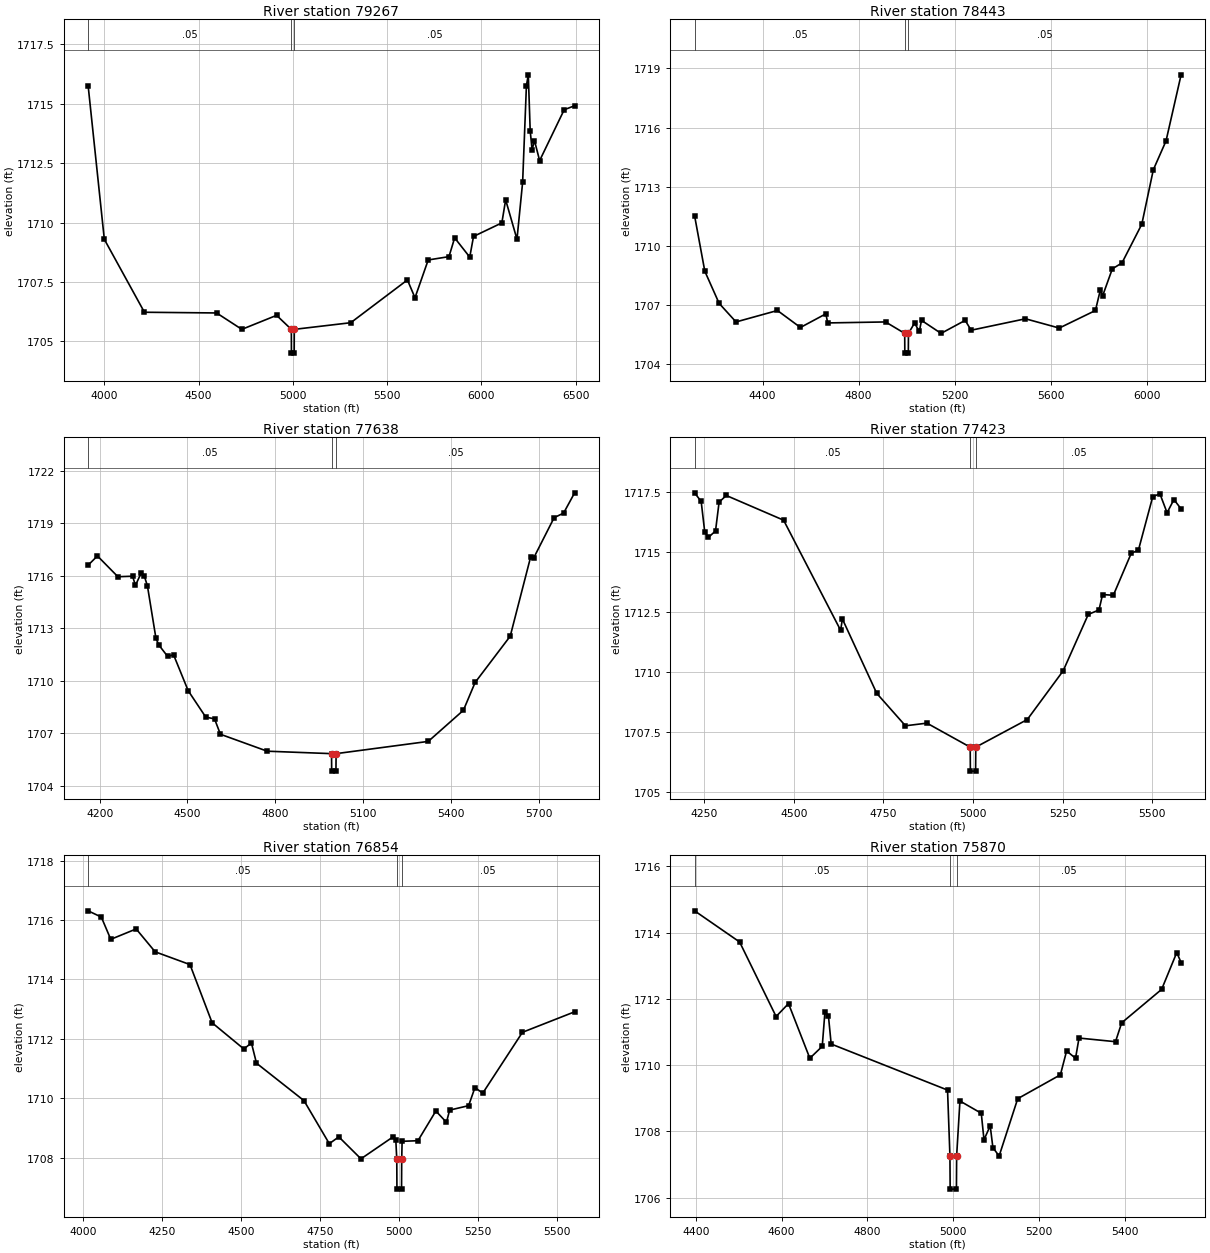
Type RM Length L Ch R = 1,79267,824,824,824
BEGIN DESCRIPTION:
Mapping XS a5e50220
END DESCRIPTION:
XS GIS Cut Line= 3
      1571508.73      6935114.92      1570792.97      6934284.04
      1570883.05      6932802.74
#Sta/Elev= 30
  3914.2 1715.77  4000.1 1709.30  4212.9 1706.23  4595.8 1706.20  4729.7 1705.51
  4914.0 1706.10  4992.2 1705.51  4992.7 1704.51  5007.3 1704.51  5007.8 1705.51
  5307.4 1705.79  5608.0 1707.59  5648.1 1706.84  5718.2 1708.43  5828.4 1708.57
  5858.5 1709.36  5938.6 1708.55  5958.6 1709.42  6108.9 1709.99  6129.0 1710.96
  6189.1 1709.30  6219.1 1711.70  6239.2 1715.77  6249.2 1716.22  6259.2 1713.87
  6269.2 1713.07  6282.0 1713.45  6309.3 1712.61  6439.5 1714.75  6494.9 1714.92
#Mann=3,-1,0
  3914.2    0.05       0  4992.2    0.05       0  5007.8    0.05       0
Bank Sta=4992.2,5007.8
Exp/Cntr=0.3,0.1

Type RM Length L Ch R = 1,78443,805,805,805
BEGIN DESCRIPTION:
Mapping XS dea7a2ce
END DESCRIPTION:
XS GIS Cut Line= 2
      1571563.76      6935039.85      1571363.56      6933022.86
#Sta/Elev= 30
  4116.8 1711.53  4159.4 1708.72  4219.1 1707.09  4289.5 1706.15  4462.0 1706.73
  4557.8 1705.87  4663.7 1706.56  4671.4 1706.10  4912.5 1706.15  4992.2 1705.57
  4992.7 1704.57  5007.3 1704.57  5007.8 1705.57  5033.1 1706.09  5053.2 1705.67
  5062.2 1706.23  5143.7 1705.57  5244.2 1706.23  5268.9 1705.73  5495.4 1706.31
  5636.1 1705.84  5786.8 1706.73  5806.9 1707.75  5817.0 1707.48  5857.2 1708.84
  5897.4 1709.14  5980.0 1711.10  6028.0 1713.86  6080.9 1715.32  6143.7 1718.67
#Mann=3,-1,0
  4116.8    0.05       0  4992.2    0.03       0  5007.8    0.05       0
Bank Sta=4992.2,5007.8
Exp/Cntr=0.3,0.1

Type RM Length L Ch R = 1,77638,215,215,215
BEGIN DESCRIPTION:
Mapping XS da46497e
END DESCRIPTION:
XS GIS Cut Line= 2
      1571984.19      6934989.78      1571949.15      6933328.05
#Sta/Elev= 30
  4160.6 1716.61  4192.4 1717.14  4262.4 1715.95  4312.4 1715.98  4322.4 1715.46
  4342.4 1716.18  4352.4 1716.00  4363.3 1715.42  4392.4 1712.42  4402.4 1712.04
  4432.4 1711.39  4452.4 1711.49  4502.5 1709.43  4562.5 1707.92  4592.5 1707.82
  4612.5 1706.94  4772.5 1705.97  4992.2 1705.83  4992.7 1704.83  5007.3 1704.83
  5007.8 1705.83  5322.6 1706.53  5442.7 1708.31  5482.7 1709.90  5602.7 1712.55
  5672.7 1717.10  5682.7 1717.02  5752.7 1719.33  5785.0 1719.59  5822.7 1720.75
#Mann=3,-1,0
  4160.6    0.05       0  4992.2    0.05       0  5007.8    0.05       0
Bank Sta=4992.2,5007.8
Exp/Cntr=0.3,0.1

Type RM Length L Ch R = 1,77423,569,569,569
BEGIN DESCRIPTION:
Mapping XS 4da86e3f
END DESCRIPTION:
XS GIS Cut Line= 2
      1572135.57      6934876.39      1572150.17      6933518.87
#Sta/Elev= 30
  4223.1 1717.48  4241.5 1717.12  4251.5 1715.84  4261.5 1715.62  4281.5 1715.89
  4291.5 1717.09  4311.5 1717.37  4471.5 1716.34  4630.6 1711.75  4635.6 1712.22
  4731.5 1709.12  4811.5 1707.77  4871.5 1707.88  4992.2 1706.88  4992.7 1705.88
  5007.3 1705.88  5007.8 1706.88  5151.5 1708.03  5251.6 1710.06  5321.6 1712.41
  5351.6 1712.60  5361.6 1713.24  5391.6 1713.21  5441.6 1714.96  5461.6 1715.09
  5501.6 1717.32  5521.6 1717.44  5541.6 1716.65  5560.7 1717.20  5580.7 1716.81
#Mann=3,-1,0
  4223.1    0.05       0  4992.2    0.03       0  5007.8    0.05       0
Bank Sta=4992.2,5007.8
Exp/Cntr=0.3,0.1

Type RM Length L Ch R = 1,76854,984,984,984
BEGIN DESCRIPTION:
Mapping XS a8a8eb47
END DESCRIPTION:
XS GIS Cut Line= 2
      1572564.78      6934969.71      1572669.88      6933433.20
#Sta/Elev= 30
  4015.1 1716.31  4056.9 1716.10  4086.8 1715.35  4167.2 1715.70  4227.3 1714.93
  4337.6 1714.50  4407.7 1712.54  4508.0 1711.66  4532.1 1711.86  4548.1 1711.18
  4698.4 1709.92  4778.6 1708.47  4808.7 1708.70  4878.8 1707.96  4979.1 1708.69
  4989.1 1708.61  4992.2 1707.94  4992.7 1706.94  5007.3 1706.94  5007.8 1707.94
  5009.1 1708.55  5059.2 1708.57  5115.9 1709.57  5149.5 1709.19  5159.5 1709.60
  5219.6 1709.75  5239.7 1710.36  5264.3 1710.17  5390.0 1712.22  5555.2 1712.91
#Mann=3,-1,0
  4015.1    0.05       0  4992.2   0.035       0  5007.8    0.05       0
Bank Sta=4992.2,5007.8
Exp/Cntr=0.3,0.1

Type RM Length L Ch R = 1,75870,349,349,349
BEGIN DESCRIPTION:
Mapping XS 34e503ac
END DESCRIPTION:
XS GIS Cut Line= 2
      1573645.87      6934394.15      1572945.19      6933503.28
#Sta/Elev= 30
  4397.3 1714.66  4502.2 1713.72  4587.2 1711.47  4616.1 1711.86  4665.8 1710.21
  4694.7 1710.57  4701.0 1711.61  4709.1 1711.49  4715.5 1710.64  4986.6 1709.25
  4992.2 1707.26  4992.7 1706.26  5007.3 1706.26  5007.8 1707.26  5015.5 1708.92
  5065.2 1708.55  5071.5 1707.75  5086.0 1708.17  5092.3 1707.51  5106.8 1707.26
  5150.1 1708.99  5249.5 1709.71  5264.0 1710.43  5284.8 1710.21  5292.9 1710.82
  5377.9 1710.71  5392.3 1711.28  5485.4 1712.29  5520.6 1713.40  5530.7 1713.10
#Mann=3,-1,0
  4397.3    0.05       0  4992.2    0.03       0  5007.8    0.05       0
Bank Sta=4992.2,5007.8
Exp/Cntr=0.3,0.1