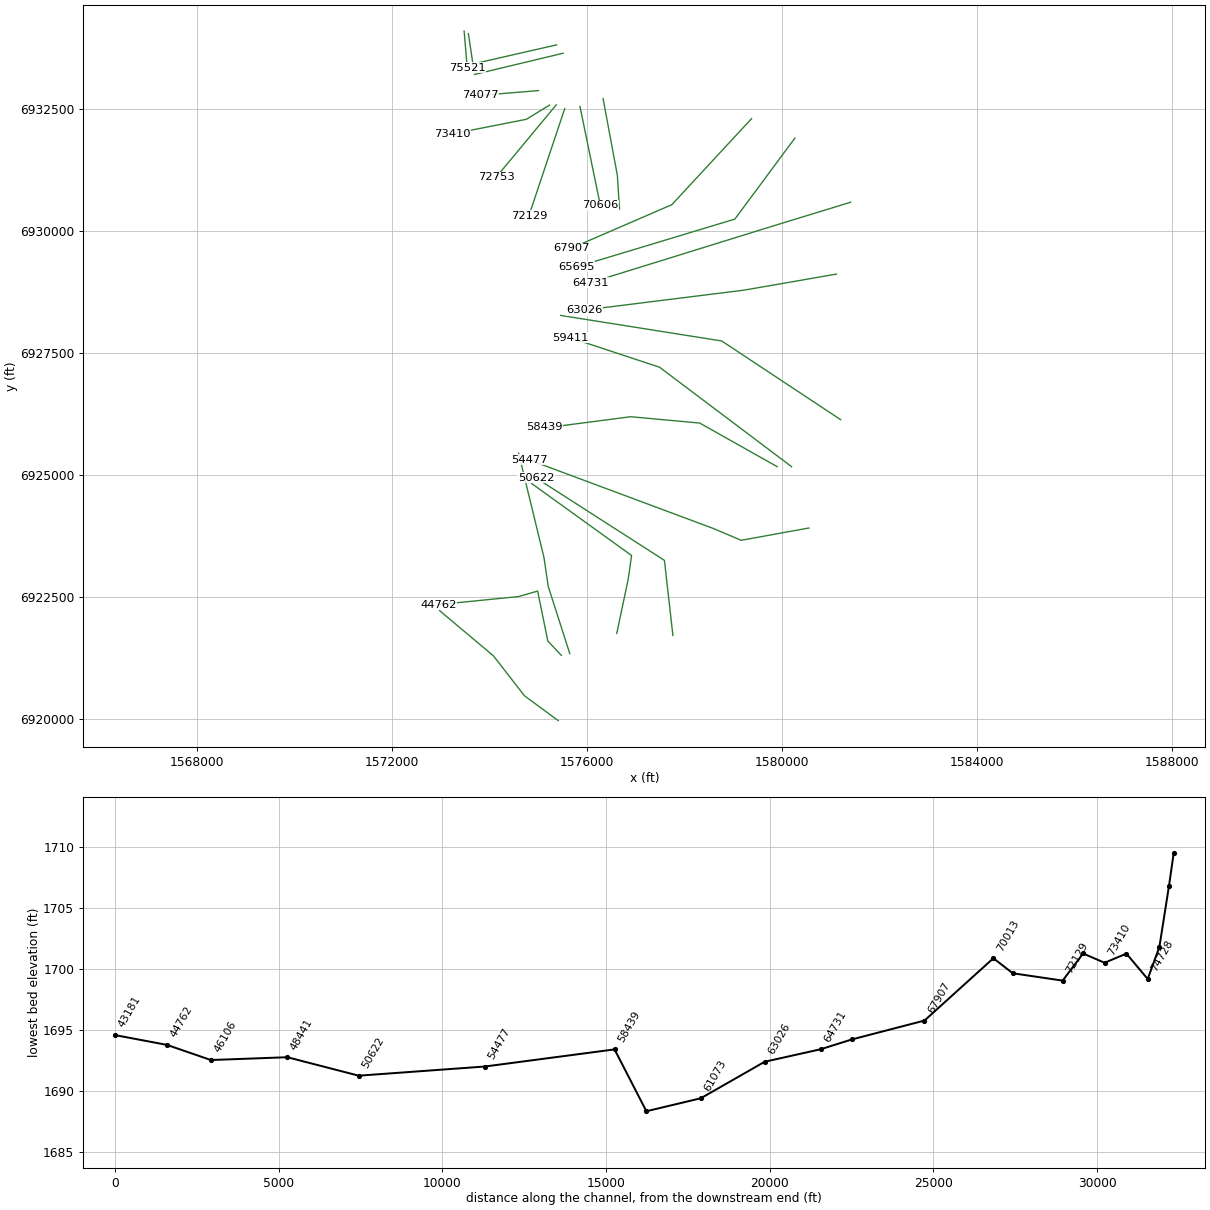
HEC-RAS study Deadman 17.prj: Deadman 17 Base Level Engineering

--- Deadman 17.g01 (geometry) --- (continued)

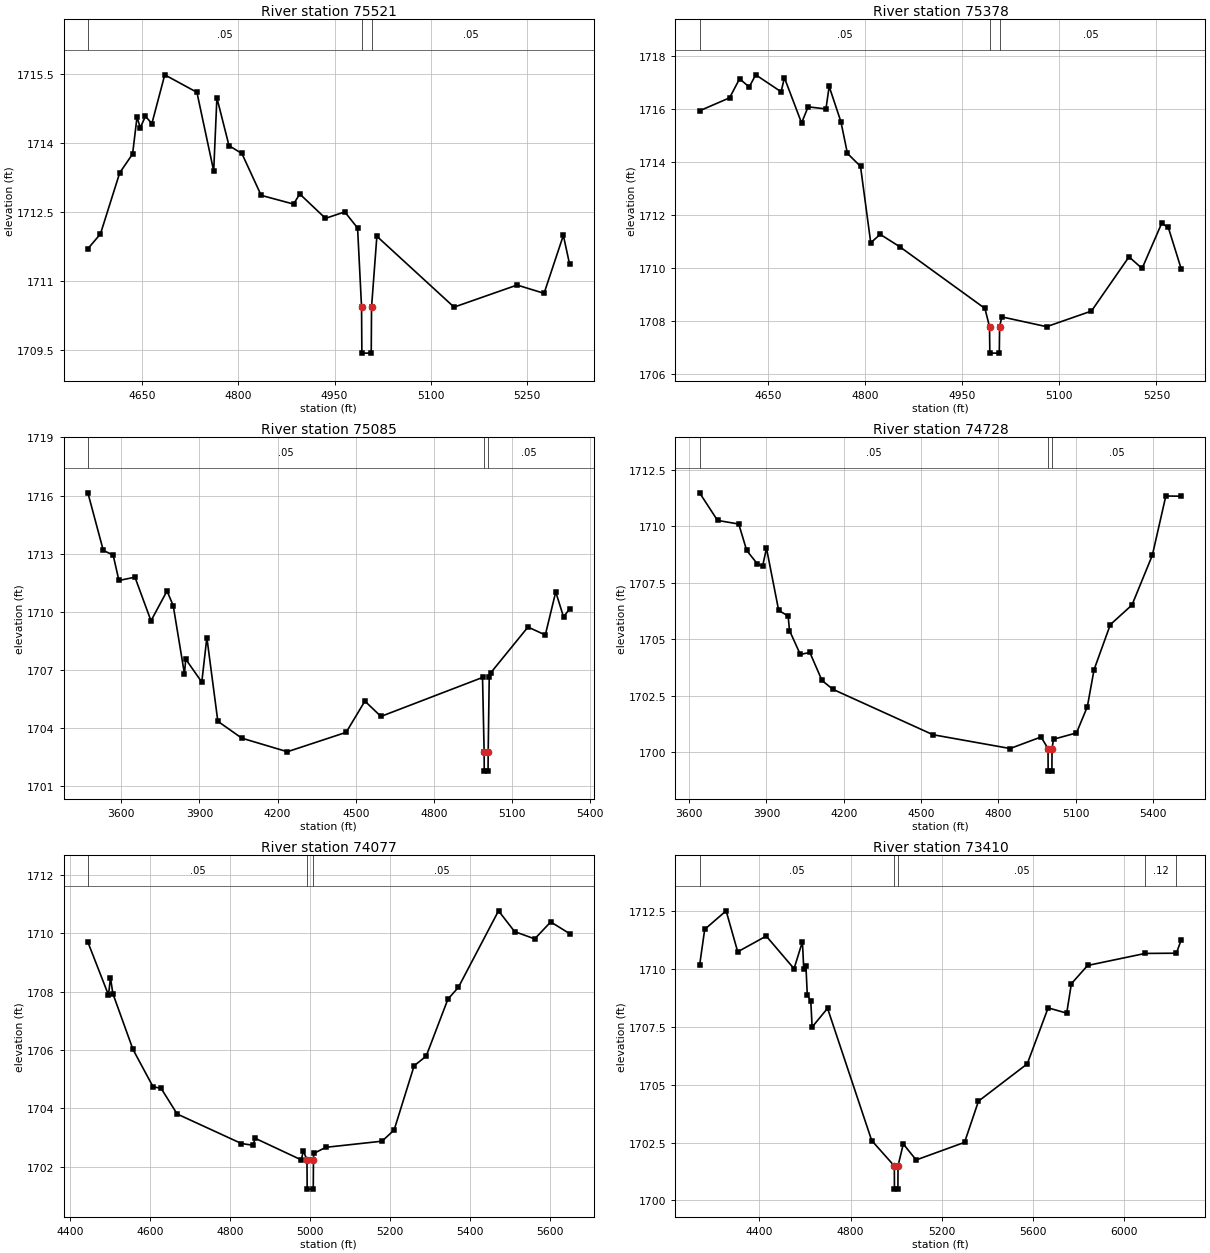
Type RM Length L Ch R = 1,75521,143,143,143
BEGIN DESCRIPTION:
Mapping XS 9b61fd76
END DESCRIPTION:
XS GIS Cut Line= 2
      1573483.38      6934107.55      1573546.64      6933358.21
#Sta/Elev= 30
  4565.0 1711.71  4584.6 1712.03  4614.7 1713.36  4634.8 1713.77  4641.7 1714.57
  4646.8 1714.34  4654.9 1714.59  4664.9 1714.43  4685.0 1715.49  4735.2 1715.11
  4761.4 1713.40  4766.4 1714.99  4785.3 1713.95  4805.4 1713.78  4835.5 1712.87
  4886.1 1712.68  4895.7 1712.90  4935.9 1712.37  4966.0 1712.51  4986.0 1712.16
  4992.2 1710.44  4992.7 1709.44  5007.3 1709.44  5007.8 1710.44  5016.1 1711.98
  5136.6 1710.44  5235.0 1710.92  5277.1 1710.74  5307.2 1712.00  5317.0 1711.37
#Mann=3,-1,0
  4565.0    0.05       0  4992.2    0.03       0  5007.8    0.05       0
Bank Sta=4992.2,5007.8
Exp/Cntr=0.3,0.1

Type RM Length L Ch R = 1,75378,293,293,293
BEGIN DESCRIPTION:
Mapping XS 602b5a74
END DESCRIPTION:
XS GIS Cut Line= 2
      1573570.80      6934053.79      1573680.91      6933318.08
#Sta/Elev= 30
  4544.5 1715.94  4590.8 1716.43  4606.3 1717.15  4621.1 1716.84  4631.2 1717.30
  4670.4 1716.66  4675.5 1717.19  4702.0 1715.48  4712.1 1716.09  4739.6 1716.01
  4744.6 1716.86  4762.7 1715.53  4772.8 1714.33  4793.0 1713.84  4808.8 1710.95
  4823.4 1711.27  4853.7 1710.80  4985.1 1708.47  4992.2 1707.78  4992.7 1706.78
  5007.3 1706.78  5007.8 1707.78  5011.2 1708.15  5080.4 1707.78  5149.6 1708.37
  5207.6 1710.42  5227.8 1709.98  5258.1 1711.69  5268.3 1711.53  5288.4 1709.95
#Mann=3,-1,0
  4544.5    0.05       0  4992.2    0.03       0  5007.8    0.05       0
Bank Sta=4992.2,5007.8
Exp/Cntr=0.3,0.1

Type RM Length L Ch R = 1,75085,357,357,357
BEGIN DESCRIPTION:
Mapping XS 383947ea
END DESCRIPTION:
XS GIS Cut Line= 3
      1575381.03      6933825.37      1573716.94      6933445.84
      1573712.07      6933304.75
#Sta/Elev= 30
  3472.2 1716.14  3531.3 1713.17  3569.2 1712.93  3591.2 1711.62  3652.8 1711.79
  3714.3 1709.54  3775.8 1711.08  3799.6 1710.32  3842.6 1706.81  3847.7 1707.56
  3909.2 1706.38  3928.6 1708.68  3970.7 1704.36  4062.7 1703.49  4237.4 1702.79
  4463.0 1703.79  4534.8 1705.40  4596.4 1704.61  4986.1 1706.62  4992.2 1702.79
  4992.7 1701.79  5007.3 1701.79  5007.8 1702.79  5011.8 1706.64  5017.0 1706.85
  5160.5 1709.22  5226.9 1708.81  5266.9 1711.03  5296.9 1709.74  5320.2 1710.16
#Mann=3,-1,0
  3472.2    0.05       0  4992.2    0.05       0  5007.8    0.05       0
Bank Sta=4992.2,5007.8
Exp/Cntr=0.3,0.1

Type RM Length L Ch R = 1,74728,651,651,651
BEGIN DESCRIPTION:
Mapping XS d8dd14fe
END DESCRIPTION:
XS GIS Cut Line= 2
      1575512.73      6933653.39      1573695.88      6933217.95
#Sta/Elev= 30
  3640.9 1711.47  3710.5 1710.25  3792.8 1710.09  3823.7 1708.92  3864.8 1708.33
  3885.4 1708.23  3900.4 1709.02  3947.6 1706.27  3984.4 1706.02  3989.6 1705.38
  4031.6 1704.32  4068.5 1704.41  4115.6 1703.17  4157.7 1702.78  4546.1 1700.77
  4845.4 1700.16  4965.1 1700.67  4992.2 1700.16  4992.7 1699.16  5007.3 1699.16
  5007.8 1700.16  5013.5 1700.57  5102.6 1700.85  5144.7 1702.01  5170.8 1703.65
  5233.8 1705.64  5317.9 1706.51  5396.8 1708.71  5449.1 1711.33  5509.2 1711.32
#Mann=3,-1,0
  3640.9    0.05       0  4992.2    0.04       0  5007.8    0.05       0
Bank Sta=4992.2,5007.8
Exp/Cntr=0.3,0.1

Type RM Length L Ch R = 1,74077,667,667,667
BEGIN DESCRIPTION:
Mapping XS 266c077f
END DESCRIPTION:
XS GIS Cut Line= 2
      1575007.22      6932887.62      1573807.97      6932787.68
#Sta/Elev= 30
  4444.6 1709.69  4496.1 1707.88  4501.1 1708.47  4507.0 1707.93  4557.2 1706.02
  4607.4 1704.74  4627.4 1704.69  4667.6 1703.81  4828.1 1702.80  4857.3 1702.74
  4862.4 1702.98  4977.7 1702.24  4982.8 1702.55  4991.9 1702.24  4992.4 1701.24
  5007.6 1701.24  5008.1 1702.24  5008.8 1702.46  5038.9 1702.67  5179.4 1702.88
  5209.5 1703.26  5259.6 1705.46  5289.7 1705.79  5344.0 1707.74  5370.0 1708.14
  5470.4 1710.76  5510.5 1710.05  5560.7 1709.80  5600.8 1710.38  5648.0 1709.98
#Mann=3,-1,0
  4444.6    0.05       0  4991.9    0.04       0  5008.1    0.05       0
Bank Sta=4991.9,5008.1
Exp/Cntr=0.3,0.1

Type RM Length L Ch R = 1,73410,657,657,657
BEGIN DESCRIPTION:
Mapping XS 2e13aa99
END DESCRIPTION:
XS GIS Cut Line= 3
      1575234.18      6932589.73      1574760.81      6932298.42
      1573231.36      6931998.00
#Sta/Elev= 30
  4137.1 1710.15  4159.6 1711.71  4253.6 1712.51  4304.5 1710.74  4429.7 1711.42
  4551.8 1710.01  4588.5 1711.18  4594.4 1709.98  4603.9 1710.13  4609.8 1708.89
  4625.2 1708.61  4631.1 1707.49  4698.8 1708.30  4892.5 1702.59  4991.9 1701.49
  4992.4 1700.49  5007.6 1700.49  5008.1 1701.49  5031.2 1702.44  5087.7 1701.75
  5300.1 1702.51  5361.3 1704.29  5575.3 1705.90  5667.0 1708.32  5748.5 1708.09
  5768.9 1709.36  5840.2 1710.15  6093.1 1710.67  6230.0 1710.68  6251.6 1711.27
#Mann=5,-1,0
  4137.1    0.05       0  4991.9    0.05       0  5008.1    0.05       0
  6093.1    0.12       0  6230.0    0.05       0
Bank Sta=4991.9,5008.1
Exp/Cntr=0.3,0.1

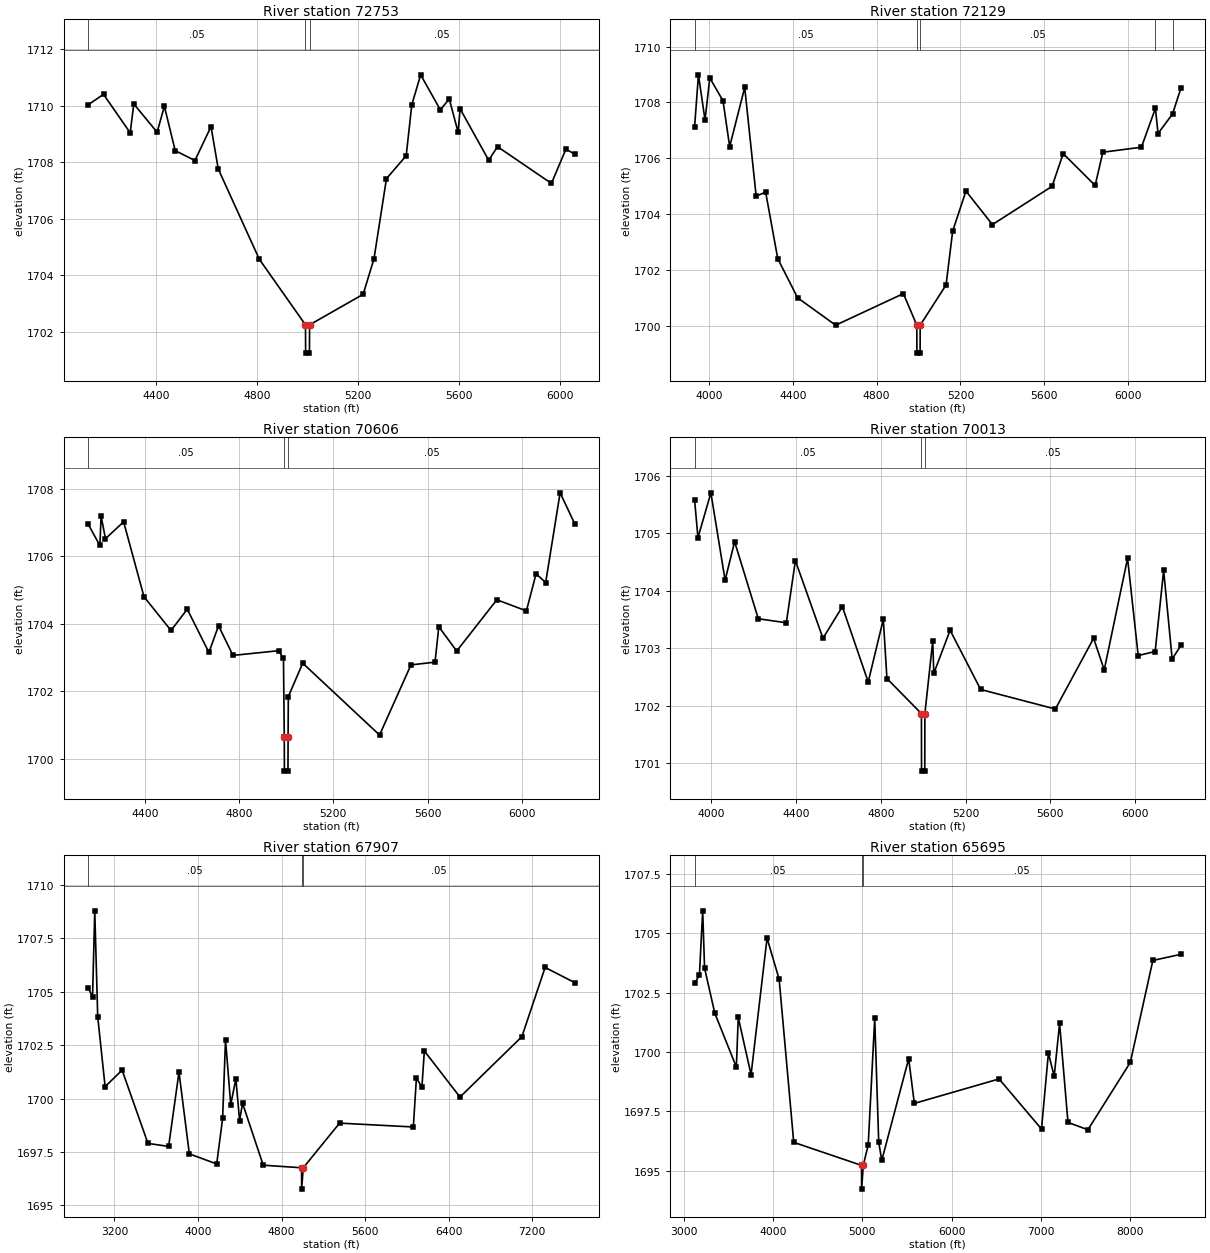
Type RM Length L Ch R = 1,72753,624,624,624
BEGIN DESCRIPTION:
Mapping XS f2311981
END DESCRIPTION:
XS GIS Cut Line= 2
      1575373.41      6932594.92      1574141.76      6931111.73
#Sta/Elev= 30
  4130.5 1710.03  4191.5 1710.40  4297.2 1709.04  4311.5 1710.06  4404.0 1709.06
  4432.6 1709.98  4475.6 1708.41  4553.7 1708.06  4617.5 1709.26  4646.2 1707.76
  4808.9 1704.57  4991.9 1702.25  4992.4 1701.25  5007.6 1701.25  5008.1 1702.25
  5220.4 1703.33  5263.4 1704.59  5312.8 1707.42  5391.0 1708.23  5413.1 1710.03
  5448.3 1711.09  5526.4 1709.85  5561.5 1710.24  5596.7 1709.06  5604.5 1709.89
  5717.8 1708.07  5752.9 1708.55  5966.5 1707.25  6023.8 1708.46  6058.4 1708.29
#Mann=3,-1,0
  4130.5    0.05       0  4991.9    0.05       0  5008.1    0.05       0
Bank Sta=4991.9,5008.1
Exp/Cntr=0.3,0.1

Type RM Length L Ch R = 1,72129,1523,1523,1523
BEGIN DESCRIPTION:
Mapping XS cdbe9e7b
END DESCRIPTION:
XS GIS Cut Line= 2
      1575547.03      6932516.81      1574809.77      6930313.70
#Sta/Elev= 30
  3930.7 1707.12  3949.1 1708.99  3980.6 1707.37  4003.3 1708.88  4066.5 1708.06
  4098.2 1706.42  4170.1 1708.54  4224.7 1704.65  4270.1 1704.79  4327.9 1702.41
  4422.7 1701.01  4604.3 1700.03  4927.8 1701.16  4991.9 1700.03  4992.4 1699.03
  5007.6 1699.03  5008.1 1700.03  5131.6 1701.47  5163.2 1703.40  5226.5 1704.83
  5353.0 1703.63  5637.8 1705.00  5690.9 1706.17  5843.5 1705.03  5880.3 1706.22
  6064.5 1706.40  6131.3 1707.79  6143.9 1706.89  6213.1 1707.59  6253.9 1708.53
#Mann=5,-1,0
  3930.7    0.05       0  4991.9    0.05       0  5008.1    0.05       0
  6131.3    0.12       0  6213.1    0.05       0
Bank Sta=4991.9,5008.1
Exp/Cntr=0.3,0.1

Type RM Length L Ch R = 1,70606,593,593,593
BEGIN DESCRIPTION:
Mapping XS 9fd31c70
END DESCRIPTION:
XS GIS Cut Line= 2
      1575859.52      6932560.18      1576276.18      6930537.65
#Sta/Elev= 30
  4159.3 1706.95  4209.3 1706.32  4214.4 1707.19  4233.0 1706.52  4310.0 1707.02
  4396.4 1704.80  4511.2 1703.80  4580.1 1704.43  4672.0 1703.15  4712.9 1703.94
  4774.1 1703.06  4968.1 1703.20  4988.5 1702.97  4991.9 1700.63  4992.4 1699.63
  5007.6 1699.63  5008.1 1700.63  5009.1 1701.84  5070.2 1702.83  5396.3 1700.70
  5529.7 1702.78  5631.8 1702.86  5647.8 1703.91  5723.7 1703.19  5894.2 1704.71
  6019.7 1704.38  6060.6 1705.48  6101.4 1705.22  6162.7 1707.88  6224.3 1706.97
#Mann=3,-1,0
  4159.3    0.05       0  4991.9    0.05       0  5008.1    0.05       0
Bank Sta=4991.9,5008.1
Exp/Cntr=0.3,0.1

Type RM Length L Ch R = 1,70013,2106,2106,2106
BEGIN DESCRIPTION:
Mapping XS 11360e43
END DESCRIPTION:
XS GIS Cut Line= 3
      1576333.43      6932723.67      1576626.40      6931150.35
      1576669.80      6930455.87
#Sta/Elev= 30
  3921.2 1705.58  3937.1 1704.92  3998.2 1705.70  4065.3 1704.18  4110.1 1704.85
  4221.9 1703.51  4354.2 1703.44  4397.0 1704.52  4527.1 1703.17  4618.7 1703.72
  4740.7 1702.41  4811.9 1703.50  4829.1 1702.47  4991.9 1701.86  4992.4 1700.86
  5007.6 1700.86  5008.1 1701.86  5045.2 1703.12  5050.3 1702.56  5127.2 1703.31
  5271.4 1702.28  5624.1 1701.94  5804.5 1703.17  5854.6 1702.62  5964.8 1704.56
  6014.9 1702.87  6095.0 1702.94  6135.1 1704.35  6175.2 1702.81  6217.4 1703.05
#Mann=3,-1,0
  3921.2    0.05       0  4991.9    0.03       0  5008.1    0.05       0
Bank Sta=4991.9,5008.1
Exp/Cntr=0.3,0.1

Type RM Length L Ch R = 1,67907,2212,2212,2212
BEGIN DESCRIPTION:
Mapping XS b70c5d0b
END DESCRIPTION:
XS GIS Cut Line= 3
      1579380.03      6932313.03      1577743.20      6930546.30
      1575677.21      6929652.20
#Sta/Elev= 30
  2947.5 1705.18  2990.1 1704.77  3011.1 1708.79  3039.4 1703.83  3110.3 1700.56
  3273.0 1701.33  3520.7 1697.90  3718.6 1697.76  3817.8 1701.24  3917.0 1697.41
  4179.0 1696.94  4235.7 1699.07  4263.5 1702.75  4313.4 1699.72  4362.7 1700.92
  4398.4 1698.97  4426.6 1699.78  4624.6 1696.88  4991.9 1696.76  4992.4 1695.76
  5008.1 1696.76  5355.9 1698.85  6062.2 1698.67  6091.9 1700.96  6144.4 1700.53
  6167.8 1702.23  6509.0 1700.07  7102.2 1702.90  7324.4 1706.14  7607.1 1705.43
#Mann=3,-1,0
  2947.5    0.05       0  4991.9   0.035       0  5008.1    0.05       0
Bank Sta=4991.9,5008.1
Exp/Cntr=0.3,0.1

Type RM Length L Ch R = 1,65695,964,964,964
BEGIN DESCRIPTION:
Mapping XS 9f18583d
END DESCRIPTION:
XS GIS Cut Line= 3
      1580267.61      6931911.63      1579036.61      6930251.16
      1575790.06      6929270.26
#Sta/Elev= 30
  3116.9 1702.89  3171.2 1703.23  3208.0 1705.94  3228.8 1703.53  3343.6 1701.63
  3585.6 1699.36  3606.9 1701.45  3750.5 1699.04  3930.0 1704.79  4065.6 1703.06
  4229.3 1696.19  4990.3 1695.22  4990.8 1694.22  5009.7 1695.22  5065.1 1696.09
  5138.1 1701.41  5182.8 1696.20  5217.1 1695.43  5519.0 1699.71  5582.6 1697.83
  6533.2 1698.86  7009.3 1696.75  7086.8 1699.95  7151.5 1698.97  7212.2 1701.20
  7306.2 1697.03  7529.7 1696.72  8006.1 1699.56  8258.4 1703.85  8575.4 1704.11
#Mann=3,-1,0
  3116.9    0.05       0  4990.3   0.035       0  5009.7    0.05       0
Bank Sta=4990.3,5009.7
Exp/Cntr=0.3,0.1

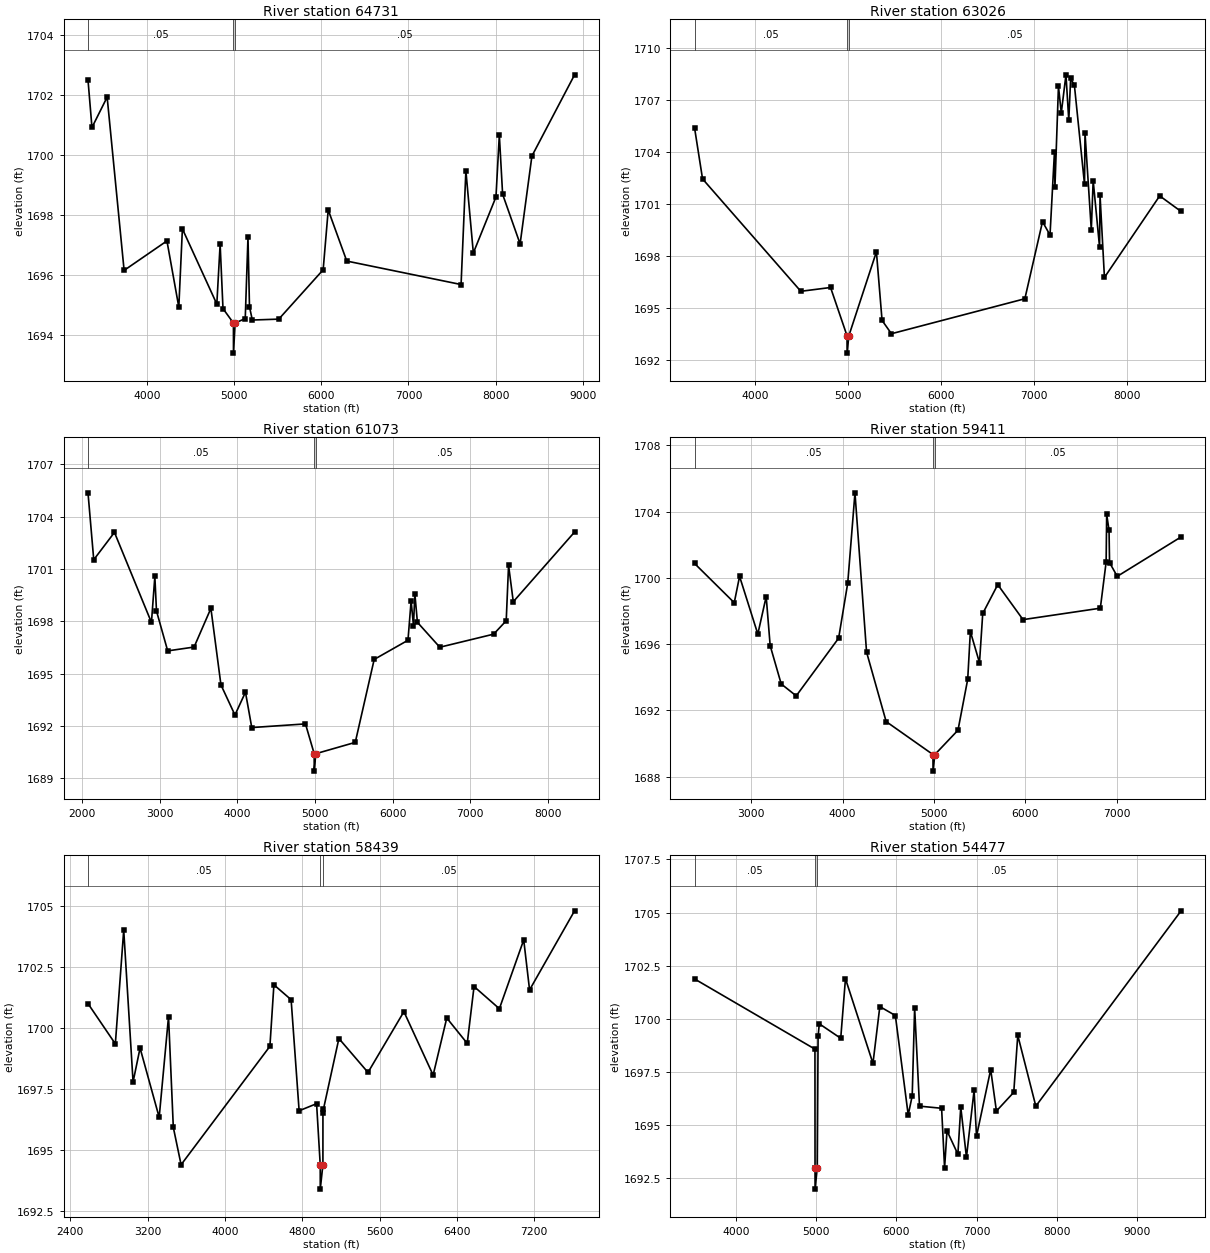
Type RM Length L Ch R = 1,64731,1705,1705,1705
BEGIN DESCRIPTION:
Mapping XS 5a3657fe
END DESCRIPTION:
XS GIS Cut Line= 3
      1581411.57      6930596.97      1579816.50      6930108.68
      1576073.05      6928947.67
#Sta/Elev= 30
  3320.1 1702.49  3365.7 1700.91  3540.0 1701.92  3734.8 1696.16  4226.7 1697.14
  4363.0 1694.94  4404.2 1697.54  4799.5 1695.04  4837.5 1697.03  4870.3 1694.89
  4990.3 1694.41  4990.8 1693.41  5009.7 1694.41  5125.9 1694.56  5157.3 1697.26
  5174.6 1694.95  5207.2 1694.51  5510.9 1694.54  6020.6 1696.18  6078.7 1698.17
  6291.8 1696.47  7604.4 1695.69  7659.6 1699.47  7745.2 1696.74  8005.1 1698.60
  8043.7 1700.66  8081.5 1698.69  8282.3 1697.04  8417.8 1699.96  8907.6 1702.66
#Mann=3,-1,0
  3320.1    0.05       0  4990.3    0.05       0  5009.7    0.05       0
Bank Sta=4990.3,5009.7
Exp/Cntr=0.3,0.1

Type RM Length L Ch R = 1,63026,1953,1953,1953
BEGIN DESCRIPTION:
Mapping XS b8676b84
END DESCRIPTION:
XS GIS Cut Line= 3
      1581119.91      6929122.69      1579218.90      6928792.83
      1575948.14      6928385.07
#Sta/Elev= 30
  3352.3 1705.41  3438.5 1702.45  4494.0 1695.96  4813.3 1696.18  4990.3 1693.39
  4990.8 1692.39  5009.7 1693.39  5305.8 1698.24  5366.3 1694.28  5467.0 1693.51
  6900.0 1695.53  7089.5 1699.98  7170.1 1699.21  7217.9 1704.01  7223.0 1701.98
  7260.8 1707.80  7291.1 1706.26  7341.4 1708.46  7371.7 1705.84  7391.8 1708.25
  7432.1 1707.85  7540.8 1702.13  7545.9 1705.11  7613.5 1699.51  7633.7 1702.35
  7702.3 1698.51  7707.3 1701.51  7754.6 1696.76  8348.1 1701.47  8577.8 1700.57
#Mann=3,-1,0
  3352.3    0.05       0  4990.3    0.05       0  5009.7    0.05       0
Bank Sta=4990.3,5009.7
Exp/Cntr=0.3,0.1

Type RM Length L Ch R = 1,61073,1662,1662,1662
BEGIN DESCRIPTION:
Mapping XS 00debe75
END DESCRIPTION:
XS GIS Cut Line= 3
      1581206.71      6926136.60      1578767.51      6927751.16
      1575465.34      6928274.92
#Sta/Elev= 30
  2075.6 1705.37  2149.6 1701.53  2416.4 1703.10  2893.1 1697.93  2936.9 1700.57
  2958.0 1698.59  3102.4 1696.30  3442.4 1696.52  3659.0 1698.74  3788.4 1694.35
  3968.9 1692.62  4104.3 1693.93  4185.5 1691.90  4877.5 1692.11  4989.8 1690.40
  4990.3 1689.40  5010.2 1690.40  5518.9 1691.05  5762.7 1695.81  6198.0 1696.91
  6238.5 1699.17  6268.9 1697.75  6286.7 1699.58  6319.5 1697.94  6608.2 1696.51
  7301.7 1697.26  7463.7 1698.03  7494.0 1701.21  7554.8 1699.12  8344.2 1703.12
#Mann=3,-1,0
  2075.6    0.05       0  4989.8    0.05       0  5010.2    0.05       0
Bank Sta=4989.8,5010.2
Exp/Cntr=0.3,0.1

Type RM Length L Ch R = 1,59411,972,972,972
BEGIN DESCRIPTION:
Mapping XS 005a0262
END DESCRIPTION:
XS GIS Cut Line= 3
      1580199.79      6925173.04      1577491.47      6927212.97
      1575651.21      6927820.60
#Sta/Elev= 30
  2378.3 1700.87  2813.3 1698.50  2871.6 1700.09  3071.5 1696.61  3163.1 1698.87
  3206.8 1695.91  3327.6 1693.60  3492.1 1692.88  3956.4 1696.36  4056.3 1699.69
  4135.4 1705.13  4262.4 1695.52  4476.9 1691.33  4989.8 1689.34  4990.3 1688.34
  5010.2 1689.34  5263.7 1690.81  5370.1 1693.88  5399.2 1696.76  5499.2 1694.88
  5534.6 1697.85  5699.1 1699.59  5975.8 1697.48  6822.5 1698.17  6886.0 1700.95
  6892.0 1703.83  6917.8 1702.88  6923.6 1700.92  7007.7 1700.09  7706.9 1702.47
#Mann=3,-1,0
  2378.3    0.05       0  4989.8   0.035       0  5010.2    0.05       0
Bank Sta=4989.8,5010.2
Exp/Cntr=0.3,0.1

Type RM Length L Ch R = 1,58439,3962,3962,3962
BEGIN DESCRIPTION:
Mapping XS 2ebb1b6b
END DESCRIPTION:
XS GIS Cut Line= 5
      1579904.69      6925173.02      1578316.12      6926067.14
      1576901.19      6926197.34      1575434.17      6926006.37
      1575121.66      6925980.33
#Sta/Elev= 30
  2582.1 1701.00  2865.2 1699.35  2951.9 1704.01  3048.7 1697.79  3121.1 1699.18
  3319.0 1696.34  3415.8 1700.47  3465.3 1695.93  3545.8 1694.40  4465.2 1699.25
  4506.6 1701.77  4684.8 1701.16  4767.6 1696.61  4948.4 1696.90  4986.1 1694.40
  4986.6 1693.40  5013.9 1694.40  5014.2 1696.51  5019.2 1696.67  5179.4 1699.57
  5480.6 1698.18  5852.3 1700.67  6154.9 1698.07  6296.0 1700.41  6507.8 1699.37
  6578.4 1701.70  6840.6 1700.79  7092.7 1703.61  7153.2 1701.56  7618.9 1704.80
#Mann=3,-1,0
  2582.1    0.05       0  4986.1    0.05       0  5013.9    0.05       0
Bank Sta=4986.1,5013.9
Exp/Cntr=0.3,0.1

Type RM Length L Ch R = 1,54477,3855,3855,3855
BEGIN DESCRIPTION:
Mapping XS 55835a42
END DESCRIPTION:
XS GIS Cut Line= 4
      1580555.67      6923914.35      1579166.81      6923662.62
      1578593.90      6923905.68      1574818.91      6925311.53
#Sta/Elev= 30
  3484.6 1701.88  4985.0 1698.58  4986.1 1693.00  4986.6 1692.00  5013.9 1693.00
  5024.0 1699.18  5039.3 1699.77  5306.1 1699.09  5365.2 1701.89  5707.7 1697.91
  5793.3 1700.58  5986.8 1700.16  6146.8 1695.49  6196.7 1696.38  6227.0 1700.52
  6287.6 1695.90  6563.0 1695.80  6600.0 1693.00  6630.3 1694.74  6765.8 1693.64
  6801.6 1695.86  6872.5 1693.50  6967.6 1696.64  6998.0 1694.49  7174.6 1697.62
  7245.9 1695.67  7461.9 1696.55  7511.9 1699.23  7736.8 1695.90  9546.7 1705.08
#Mann=3,-1,0
  3484.6    0.05       0  4986.1    0.03       0  5013.9    0.05       0
Bank Sta=4986.1,5013.9
Exp/Cntr=0.3,0.1

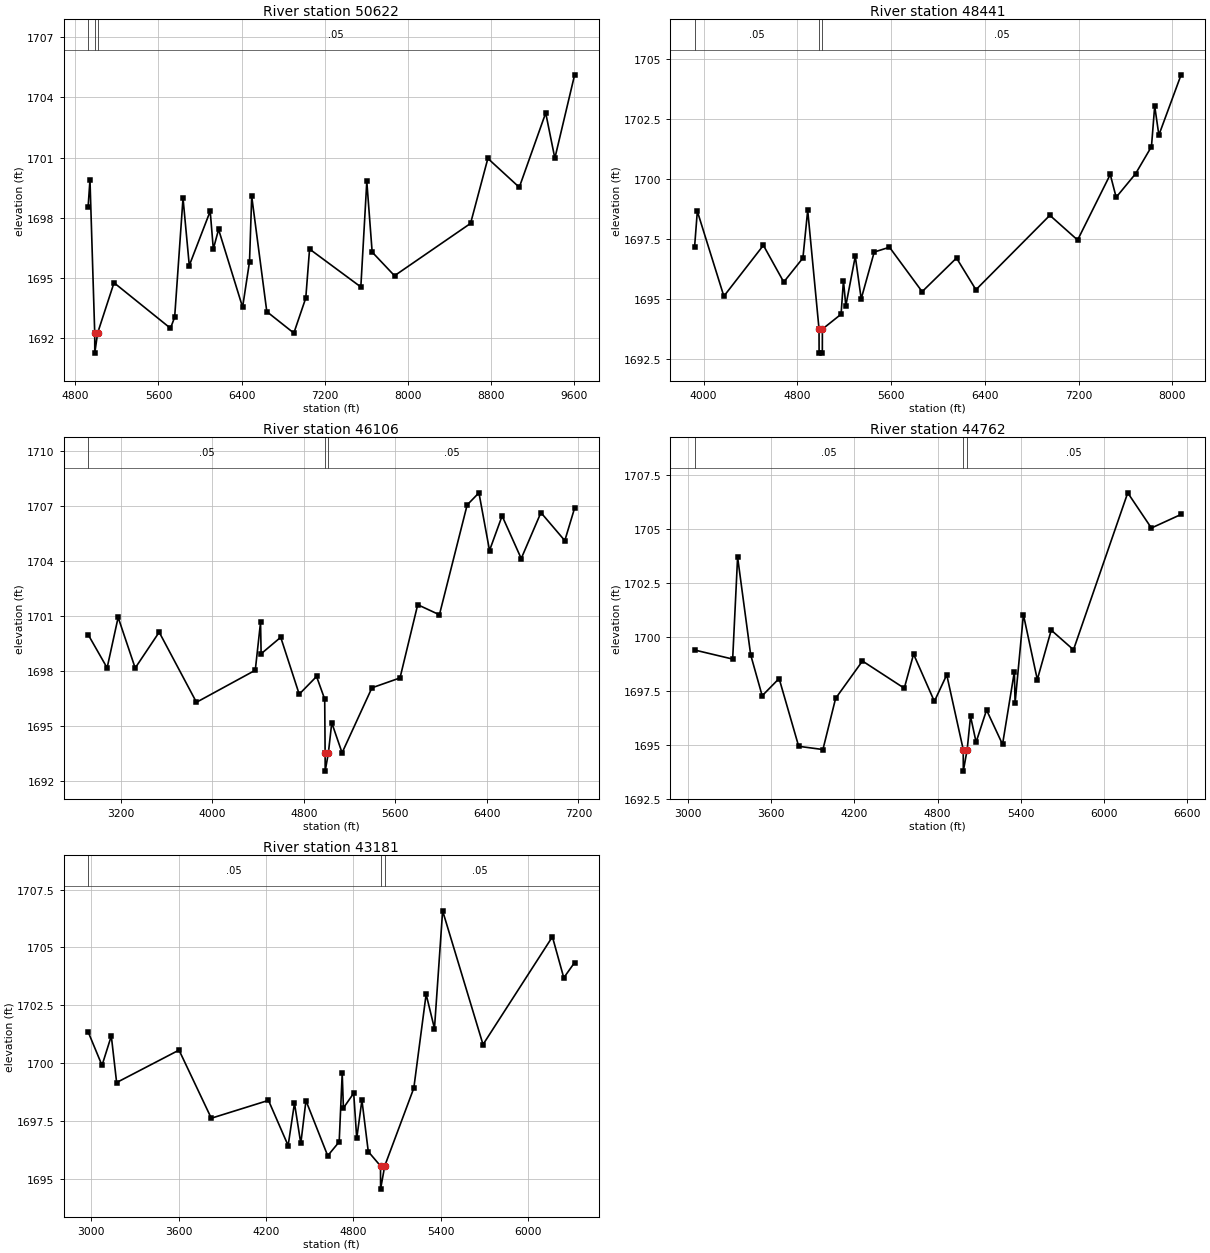
Type RM Length L Ch R = 1,50622,2181,2181,2181
BEGIN DESCRIPTION:
Mapping XS b219fec3
END DESCRIPTION:
XS GIS Cut Line= 3
      1577765.72      6921710.23      1577592.11      6923251.04
      1574955.94      6924943.39
#Sta/Elev= 30
  4922.5 1698.55  4940.4 1699.89  4986.1 1692.25  4986.6 1691.25  5013.9 1692.25
  5171.8 1694.76  5715.3 1692.49  5755.5 1693.04  5836.0 1698.98  5896.4 1695.62
  6097.7 1698.33  6127.8 1696.44  6178.2 1697.42  6409.6 1693.54  6476.1 1695.81
  6497.3 1699.07  6642.6 1693.32  6902.9 1692.25  7017.8 1694.00  7054.2 1696.44
  7547.7 1694.55  7605.2 1699.81  7656.7 1696.29  7871.9 1695.11  8604.0 1697.72
  8770.5 1700.96  9073.1 1699.52  9327.4 1703.23  9415.3 1700.97  9605.7 1705.13
#Mann=3,-1,0
  4922.5    0.05       0  4986.1    0.05       0  5013.9    0.05       0
Bank Sta=4986.1,5013.9
Exp/Cntr=0.3,0.1

Type RM Length L Ch R = 1,48441,2335,2335,2335
BEGIN DESCRIPTION:
Mapping XS 02366807
END DESCRIPTION:
XS GIS Cut Line= 4
      1576614.45      6921753.60      1576848.84      6922864.76
      1576918.28      6923350.87      1574869.85      6924826.43
#Sta/Elev= 30
  3923.8 1697.18  3947.2 1698.67  4173.6 1695.13  4510.8 1697.25  4684.6 1695.72
  4848.1 1696.72  4889.0 1698.71  4985.7 1693.76  4986.2 1692.76  5013.8 1692.76
  5014.3 1693.76  5173.8 1694.38  5194.0 1695.78  5214.2 1694.73  5295.0 1696.79
  5345.5 1695.02  5456.6 1696.97  5586.8 1697.17  5865.4 1695.32  6158.7 1696.72
  6324.4 1695.40  6955.2 1698.50  7192.0 1697.47  7470.6 1700.20  7520.9 1699.25
  7686.6 1700.23  7822.2 1701.36  7849.8 1703.05  7885.4 1701.84  8075.0 1704.35
#Mann=3,-1,0
  3923.8    0.05       0  4985.7    0.03       0  5014.3    0.05       0
Bank Sta=4985.7,5014.3
Exp/Cntr=0.3,0.1

Type RM Length L Ch R = 1,46106,1344,1344,1344
BEGIN DESCRIPTION:
Mapping XS 15cfe02e
END DESCRIPTION:
XS GIS Cut Line= 4
      1575651.18      6921336.26      1575208.48      6922716.44
      1575121.67      6923306.72      1574600.84      6925450.80
#Sta/Elev= 30
  2914.1 1699.99  3080.2 1698.17  3176.6 1700.93  3325.5 1698.16  3535.2 1700.12
  3861.1 1696.29  4375.2 1698.04  4421.3 1700.66  4426.3 1698.94  4597.6 1699.84
  4759.3 1696.73  4910.9 1697.70  4982.1 1696.46  4985.7 1693.53  4986.2 1692.53
  5014.3 1693.53  5043.8 1695.17  5134.0 1693.53  5394.9 1697.08  5640.3 1697.62
  5795.0 1701.62  5984.7 1701.07  6227.3 1707.07  6330.2 1707.73  6422.8 1704.58
  6532.8 1706.47  6699.8 1704.14  6872.0 1706.65  7080.8 1705.12  7166.6 1706.90
#Mann=3,-1,0
  2914.1    0.05       0  4985.7    0.05       0  5014.3    0.05       0
Bank Sta=4985.7,5014.3
Exp/Cntr=0.3,0.1

Type RM Length L Ch R = 1,44762,1581,1581,1581
BEGIN DESCRIPTION:
Mapping XS 54e417ab
END DESCRIPTION:
XS GIS Cut Line= 5
      1575477.55      6921301.54      1575199.80      6921596.65
      1574991.47      6922620.95      1574600.84      6922508.11
      1572951.50      6922343.17
#Sta/Elev= 30
  3044.9 1699.38  3320.0 1698.96  3355.7 1703.68  3450.0 1699.16  3533.2 1697.26
  3655.6 1698.06  3796.9 1694.92  3972.0 1694.77  4063.8 1697.14  4257.7 1698.87
  4559.8 1697.61  4627.0 1699.19  4777.2 1697.00  4866.5 1698.23  4985.7 1694.77
  4986.2 1693.77  5014.3 1694.77  5038.5 1696.31  5078.7 1695.11  5154.2 1696.60
  5269.7 1695.01  5355.2 1698.38  5360.3 1696.92  5420.4 1701.02  5520.9 1698.01
  5621.4 1700.30  5782.2 1699.39  6174.2 1706.66  6345.0 1705.03  6559.6 1705.66
#Mann=3,-1,0
  3044.9    0.05       0  4985.7    0.05       0  5014.3    0.05       0
Bank Sta=4985.7,5014.3
Exp/Cntr=0.3,0.1

Type RM Length L Ch R = 1,43181,823,823,823
BEGIN DESCRIPTION:
Mapping XS 9cd1b707
END DESCRIPTION:
XS GIS Cut Line= 4
      1575413.09      6919963.70      1574720.36      6920474.13
      1574084.95      6921291.84      1572980.78      6922218.93
#Sta/Elev= 30
  2979.5 1701.36  3074.9 1699.91  3138.6 1701.18  3175.1 1699.17  3603.2 1700.57
  3824.6 1697.63  4216.9 1698.40  4351.8 1696.45  4395.2 1698.28  4438.7 1696.54
  4474.0 1698.39  4623.3 1696.01  4702.0 1696.61  4722.8 1699.57  4731.0 1698.07
  4801.6 1698.71  4822.4 1696.76  4858.0 1698.41  4901.6 1696.19  4985.5 1695.57
  4986.0 1694.57  5014.5 1695.57  5214.0 1698.93  5298.5 1702.98  5355.7 1701.50
  5411.7 1706.58  5688.8 1700.81  6164.9 1705.46  6242.9 1703.69  6317.3 1704.35
#Mann=3,-1,0
  2979.5    0.05       0  4985.5    0.05       0  5014.5    0.05       0
Bank Sta=4985.5,5014.5
Exp/Cntr=0.3,0.1