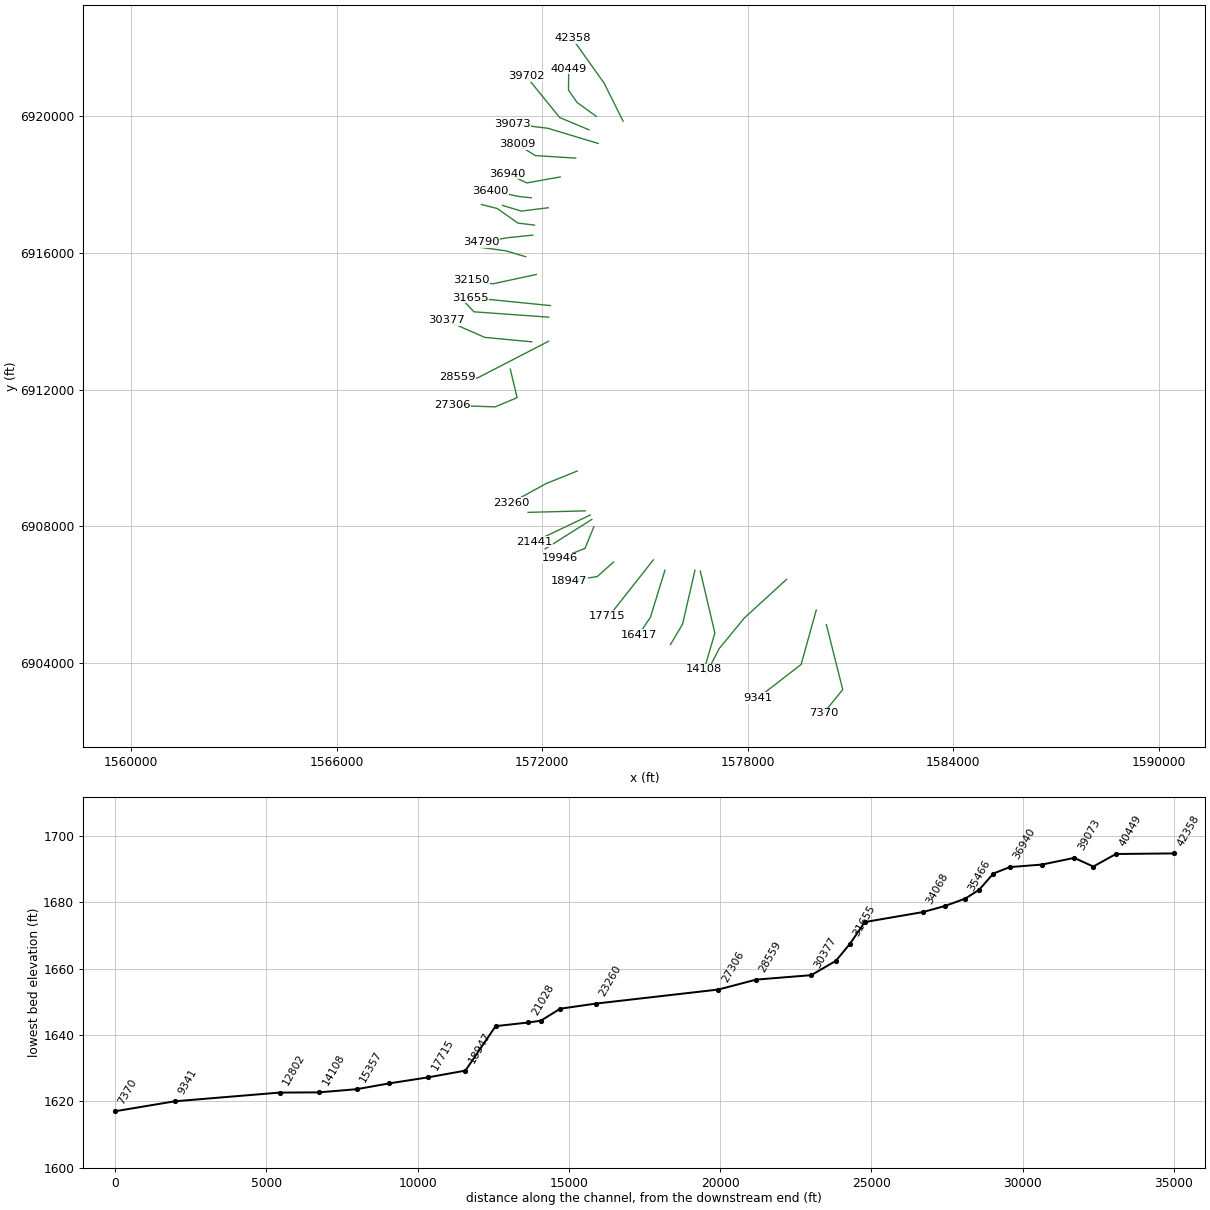
HEC-RAS study Deadman 17.prj: Deadman 17 Base Level Engineering

--- Deadman 17.g01 (geometry) --- (continued)

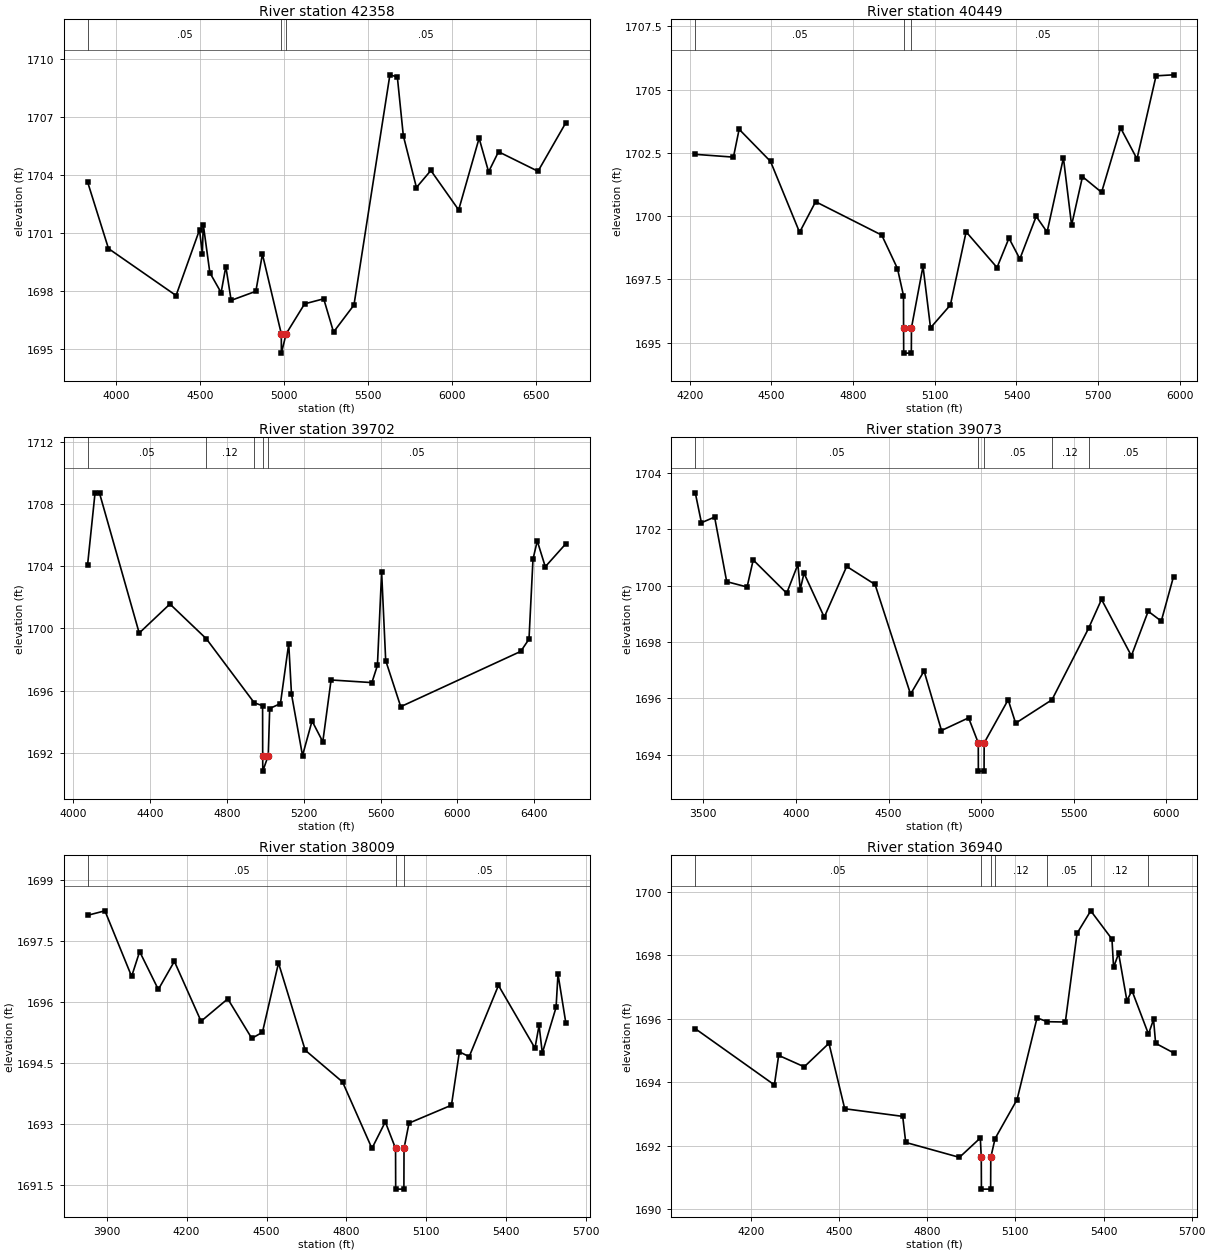
Type RM Length L Ch R = 1,42358,1909,1909,1909
BEGIN DESCRIPTION:
Deadman 17 25.0
END DESCRIPTION:
XS GIS Cut Line= 3
      1574366.45      6919843.22      1573810.91      6920954.29
      1572880.02      6922262.97
#Sta/Elev= 30
  3831.8 1703.63  3956.3 1700.18  4358.8 1697.75  4498.5 1701.15  4515.3 1699.91
  4520.9 1701.42  4560.0 1698.93  4627.1 1697.90  4655.1 1699.25  4686.9 1697.50
  4833.9 1697.97  4873.1 1699.89  4985.5 1695.77  4986.0 1694.77  5014.5 1695.77
  5124.4 1697.32  5238.1 1697.58  5296.6 1695.86  5418.3 1697.26  5632.3 1709.17
  5676.6 1709.06  5712.2 1706.02  5790.3 1703.34  5876.2 1704.22  6041.8 1702.18
  6163.6 1705.89  6220.1 1704.15  6279.2 1705.19  6514.4 1704.18  6680.0 1706.69
#Mann=3,-1,0
  3831.8    0.05       0  4985.5    0.05       0  5014.5    0.05       0
Bank Sta=4985.5,5014.5
Exp/Cntr=0.3,0.1

Type RM Length L Ch R = 1,40449,747,747,747
BEGIN DESCRIPTION:
Deadman 17 24.0
END DESCRIPTION:
XS GIS Cut Line= 4
      1573585.20      6919982.07      1573020.98      6920390.05
      1572771.57      6920751.98      1572778.02      6921372.23
#Sta/Elev= 30
  4220.7 1702.44  4360.8 1702.33  4381.7 1703.43  4497.0 1702.16  4603.7 1699.36
  4662.5 1700.57  4905.4 1699.25  4963.1 1697.93  4985.2 1696.86  4985.5 1695.59
  4986.0 1694.59  5014.0 1694.59  5014.5 1695.59  5056.9 1698.02  5084.5 1695.59
  5157.4 1696.49  5215.2 1699.38  5328.7 1697.97  5372.5 1699.13  5412.5 1698.31
  5472.5 1699.99  5512.5 1699.37  5572.5 1702.30  5602.5 1699.64  5642.5 1701.56
  5712.6 1700.94  5782.6 1703.48  5842.6 1702.26  5912.6 1705.54  5976.8 1705.58
#Mann=3,-1,0
  4220.7    0.05       0  4985.5    0.05       0  5014.5    0.05       0
Bank Sta=4985.5,5014.5
Exp/Cntr=0.3,0.1

Type RM Length L Ch R = 1,39702,629,629,629
BEGIN DESCRIPTION:
Deadman 17 23.0
END DESCRIPTION:
XS GIS Cut Line= 3
      1573370.43      6919589.89      1572514.71      6919949.39
      1571530.01      6921162.98
#Sta/Elev= 30
  4073.4 1704.09  4112.3 1708.73  4136.0 1708.69  4342.3 1699.70  4502.3 1701.57
  4692.1 1699.33  4941.5 1695.21  4985.0 1695.02  4985.5 1691.81  4986.0 1690.81
  5014.5 1691.81  5022.0 1694.84  5078.0 1695.16  5121.1 1699.02  5135.5 1695.77
  5192.9 1691.81  5242.6 1694.04  5298.6 1692.70  5341.7 1696.68  5554.3 1696.51
  5583.1 1697.62  5605.0 1703.63  5626.2 1697.93  5704.5 1694.96  6329.5 1698.52
  6372.6 1699.31  6393.4 1704.46  6415.7 1705.63  6457.4 1703.97  6564.4 1705.45
#Mann=5,-1,0
  4073.4    0.05       0  4692.1    0.12       0  4941.5    0.05       0
  4985.5    0.05       0  5014.5    0.05       0
Bank Sta=4985.5,5014.5
Exp/Cntr=0.3,0.1

Type RM Length L Ch R = 1,39073,1064,1064,1064
BEGIN DESCRIPTION:
Mapping XS c9daa355
END DESCRIPTION:
XS GIS Cut Line= 3
      1573637.35      6919192.12      1572170.29      6919634.84
      1571129.29      6919764.97
#Sta/Elev= 30
  3456.6 1703.29  3489.7 1702.23  3560.9 1702.43  3626.2 1700.14  3736.2 1699.95
  3769.2 1700.91  3950.0 1699.73  4010.4 1700.75  4023.1 1699.86  4043.4 1700.44
  4152.8 1698.88  4273.8 1700.68  4427.0 1700.04  4618.5 1696.15  4691.6 1696.97
  4785.6 1694.86  4931.9 1695.31  4984.1 1694.42  4984.6 1693.42  5015.4 1693.42
  5015.9 1694.42  5145.5 1695.95  5185.8 1695.12  5381.9 1695.95  5579.2 1698.48
  5649.4 1699.51  5810.6 1697.51  5901.3 1699.09  5971.9 1698.74  6038.1 1700.32
#Mann=5,-1,0
  3456.6    0.05       0  4984.1    0.05       0  5015.9    0.05       0
  5381.9    0.12       0  5579.2    0.05       0
Bank Sta=4984.1,5015.9
Exp/Cntr=0.3,0.1

Type RM Length L Ch R = 1,38009,1069,1069,1069
BEGIN DESCRIPTION:
Deadman 17 22.0
END DESCRIPTION:
XS GIS Cut Line= 3
      1572980.00      6918763.00      1571805.00      6918838.00
      1571280.04      6919162.97
#Sta/Elev= 30
  3828.3 1698.13  3893.4 1698.24  3993.6 1696.63  4023.7 1697.24  4093.8 1696.31
  4154.0 1697.00  4254.2 1695.53  4354.4 1696.08  4444.6 1695.11  4484.6 1695.26
  4544.8 1696.96  4645.0 1694.82  4785.2 1694.04  4895.5 1692.41  4945.6 1693.06
  4984.1 1692.41  4984.6 1691.41  5015.4 1691.41  5015.9 1692.41  5034.6 1693.03
  5193.9 1693.47  5223.7 1694.78  5260.4 1694.66  5370.3 1696.41  5507.3 1694.87
  5522.7 1695.43  5534.9 1694.75  5586.5 1695.87  5593.7 1696.69  5623.1 1695.49
#Mann=3,-1,0
  3828.3    0.05       0  4984.1    0.05       0  5015.9    0.05       0
Bank Sta=4984.1,5015.9
Exp/Cntr=0.3,0.1

Type RM Length L Ch R = 1,36940,540,540,540
BEGIN DESCRIPTION:
Deadman 17 21.0
END DESCRIPTION:
XS GIS Cut Line= 3
      1572530.03      6918213.01      1571555.00      6918038.00
      1570979.99      6918313.00
#Sta/Elev= 30
  4010.3 1695.69  4279.6 1693.92  4294.1 1694.85  4381.2 1694.49  4465.3 1695.23
  4519.0 1693.17  4716.4 1692.93  4726.6 1692.11  4909.5 1691.64  4980.6 1692.25
  4983.8 1691.64  4984.3 1690.64  5015.7 1690.64  5016.2 1691.64  5030.8 1692.23
  5105.7 1693.46  5173.7 1696.03  5208.4 1695.91  5270.0 1695.90  5309.8 1698.69
  5356.5 1699.40  5428.7 1698.51  5434.2 1697.62  5451.4 1698.06  5479.6 1696.57
  5496.7 1696.89  5553.0 1695.52  5570.3 1695.98  5577.3 1695.23  5638.3 1694.93
#Mann=7,-1,0
  4010.3    0.05       0  4983.8    0.05       0  5016.2    0.05       0
  5030.8    0.12       0  5208.4    0.05       0  5356.5    0.12       0
  5553.0    0.05       0
Bank Sta=4983.8,5016.2
Exp/Cntr=0.3,0.1

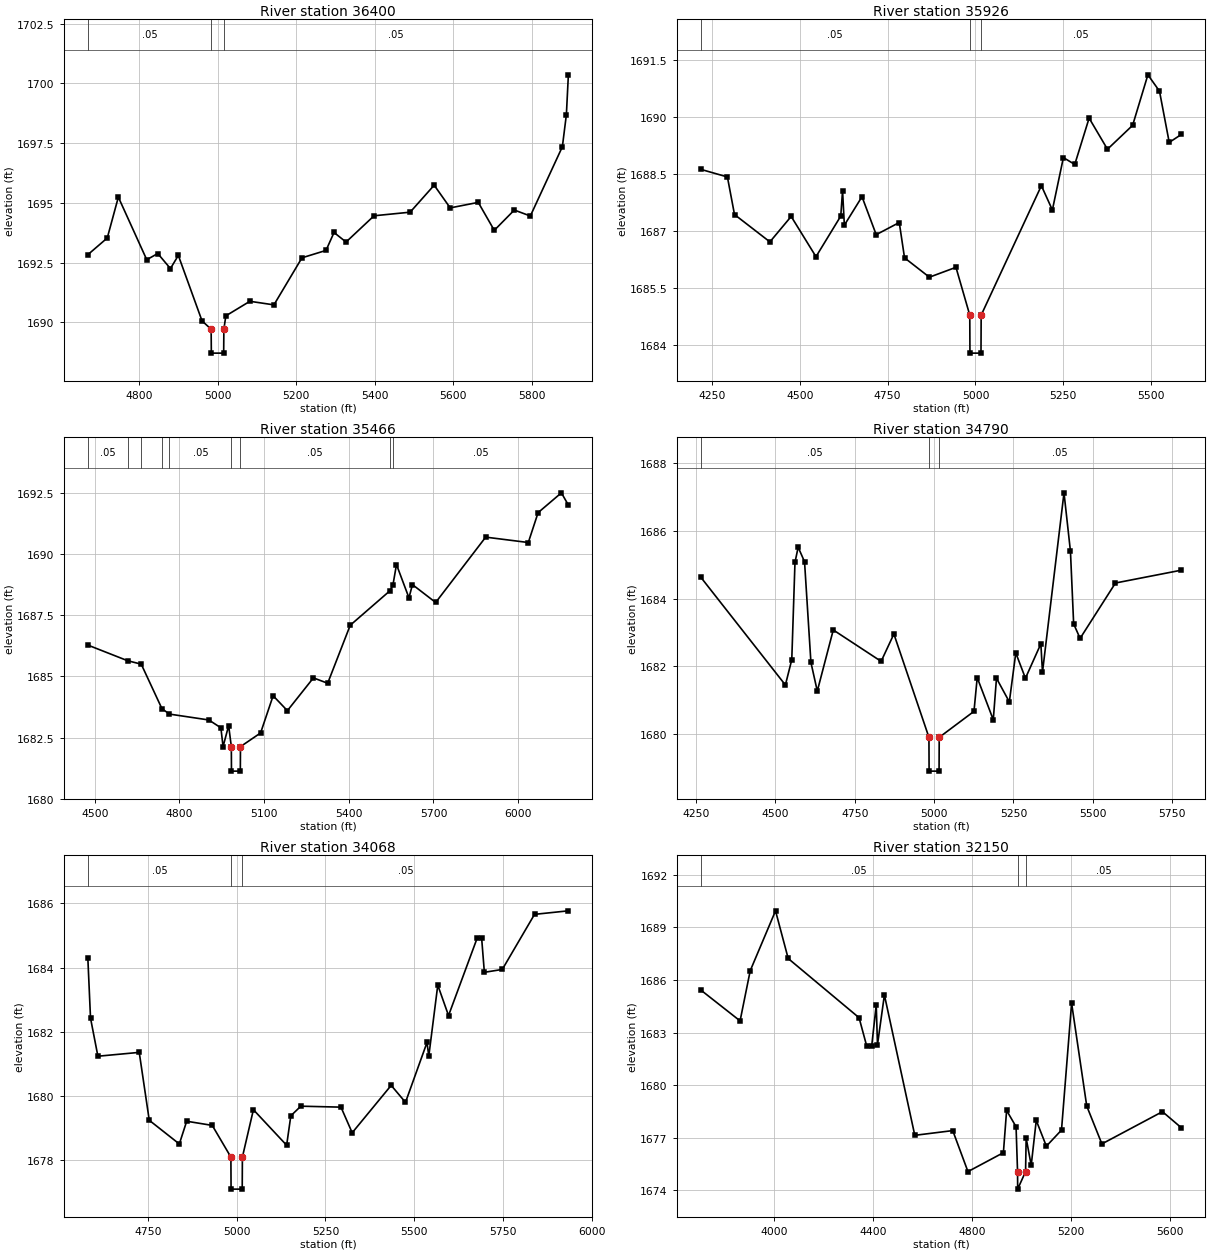
Type RM Length L Ch R = 1,36400,474,474,474
BEGIN DESCRIPTION:
Deadman 17 20.0
END DESCRIPTION:
XS GIS Cut Line= 3
      1571684.26      6917604.92      1571355.00      6917638.00
      1570480.04      6917812.99
#Sta/Elev= 30
  4669.9 1692.83  4719.4 1693.53  4747.6 1695.24  4819.9 1692.62  4847.9 1692.88
  4880.2 1692.25  4900.3 1692.80  4960.6 1690.06  4983.8 1689.71  4984.3 1688.71
  5015.7 1688.71  5016.2 1689.71  5021.2 1690.27  5082.4 1690.88  5143.6 1690.73
  5215.0 1692.70  5276.2 1693.01  5296.6 1693.76  5327.2 1693.36  5398.5 1694.46
  5490.3 1694.61  5551.5 1695.74  5592.3 1694.79  5663.7 1695.02  5704.5 1693.85
  5755.5 1694.70  5796.3 1694.45  5877.8 1697.35  5888.0 1698.69  5893.1 1700.36
#Mann=3,-1,0
  4669.9    0.05       0  4983.8    0.05       0  5016.2    0.05       0
Bank Sta=4983.8,5016.2
Exp/Cntr=0.3,0.1

Type RM Length L Ch R = 1,35926,460,460,460
BEGIN DESCRIPTION:
Deadman 17 19.0
END DESCRIPTION:
XS GIS Cut Line= 3
      1572180.01      6917313.00      1571395.64      6917215.02
      1570843.75      6917382.10
#Sta/Elev= 30
  4218.7 1688.62  4294.3 1688.42  4314.5 1687.43  4415.2 1686.71  4475.7 1687.38
  4546.3 1686.32  4616.8 1687.39  4621.9 1688.06  4627.0 1687.15  4677.2 1687.90
  4717.6 1686.90  4783.2 1687.22  4798.2 1686.29  4868.9 1685.78  4944.5 1686.04
  4983.8 1684.78  4984.3 1683.78  5015.7 1683.78  5016.2 1684.78  5187.5 1688.19
  5218.8 1687.55  5250.1 1688.93  5282.5 1688.75  5323.3 1689.97  5375.5 1689.15
  5447.1 1689.78  5490.5 1691.11  5523.5 1690.68  5551.2 1689.33  5585.8 1689.54
#Mann=3,-1,0
  4218.7    0.05       0  4983.8    0.05       0  5016.2    0.05       0
Bank Sta=4983.8,5016.2
Exp/Cntr=0.3,0.1

Type RM Length L Ch R = 1,35466,676,676,676
BEGIN DESCRIPTION:
Mapping XS 8fea24eb
END DESCRIPTION:
XS GIS Cut Line= 4
      1571780.50      6916804.86      1571294.37      6916865.62
      1570691.79      6917290.97      1570230.97      6917407.44
#Sta/Elev= 30
  4475.3 1686.28  4616.5 1685.64  4664.6 1685.50  4738.0 1683.68  4764.7 1683.46
  4904.1 1683.22  4946.8 1682.90  4954.5 1682.13  4974.3 1682.99  4983.8 1682.13
  4984.3 1681.13  5015.7 1681.13  5016.2 1682.13  5087.5 1682.69  5131.9 1684.21
  5182.4 1683.60  5274.7 1684.94  5325.2 1684.72  5405.1 1687.09  5546.0 1688.50
  5556.4 1688.73  5569.0 1689.57  5613.2 1688.21  5625.6 1688.75  5707.9 1688.02
  5885.1 1690.69  6036.1 1690.47  6070.8 1691.69  6153.3 1692.50  6178.1 1692.00
#Mann=9,-1,0
  4475.3    0.05       0  4616.5    0.12       0  4664.6    0.05       0
  4738.0    0.12       0  4764.7    0.05       0  4983.8    0.05       0
  5016.2    0.05       0  5546.0    0.12       0  5556.4    0.05       0
Bank Sta=4983.8,5016.2
Exp/Cntr=0.3,0.1

Type RM Length L Ch R = 1,34790,722,722,722
BEGIN DESCRIPTION:
Deadman 17 18.0
END DESCRIPTION:
XS GIS Cut Line= 3
      1571729.98      6916513.00      1571005.00      6916438.00
      1570229.96      6916312.99
#Sta/Elev= 30
  4265.2 1684.63  4531.6 1681.44  4551.7 1682.19  4561.8 1685.07  4571.8 1685.52
  4591.9 1685.09  4612.0 1682.11  4632.1 1681.26  4682.4 1683.07  4833.2 1682.14
  4873.4 1682.95  4983.8 1679.89  4984.3 1678.89  5015.7 1678.89  5016.2 1679.89
  5125.7 1680.66  5135.9 1681.66  5186.5 1680.41  5196.6 1681.64  5237.1 1680.94
  5257.4 1682.39  5287.8 1681.64  5336.4 1682.66  5341.5 1681.82  5409.3 1687.13
  5429.6 1685.40  5439.7 1683.25  5460.0 1682.82  5571.4 1684.46  5779.1 1684.84
#Mann=3,-1,0
  4265.2    0.05       0  4983.8    0.05       0  5016.2    0.05       0
Bank Sta=4983.8,5016.2
Exp/Cntr=0.3,0.1

Type RM Length L Ch R = 1,34068,1918,1918,1918
BEGIN DESCRIPTION:
Mapping XS 4f95076d
END DESCRIPTION:
XS GIS Cut Line= 3
      1571522.27      6915883.26      1570934.85      6916055.44
      1570200.63      6916156.71
#Sta/Elev= 30
  4580.9 1684.31  4588.5 1682.42  4609.3 1681.23  4725.7 1681.35  4753.9 1679.23
  4838.6 1678.49  4859.3 1679.20  4931.3 1679.07  4983.8 1678.08  4984.3 1677.08
  5015.7 1677.08  5016.2 1678.08  5047.2 1679.56  5140.8 1678.45  5152.6 1679.37
  5180.8 1679.67  5293.8 1679.64  5325.4 1678.84  5435.2 1680.32  5475.5 1679.79
  5536.1 1681.66  5541.1 1681.23  5566.4 1683.45  5596.7 1682.50  5677.4 1684.92
  5690.0 1684.91  5697.6 1683.85  5748.1 1683.94  5838.9 1685.66  5934.2 1685.77
#Mann=3,-1,0
  4580.9    0.05       0  4983.8    0.05       0  5016.2    0.05       0
Bank Sta=4983.8,5016.2
Exp/Cntr=0.3,0.1

Type RM Length L Ch R = 1,32150,495,495,495
BEGIN DESCRIPTION:
Deadman 17 17.0
END DESCRIPTION:
XS GIS Cut Line= 3
      1571830.03      6915363.01      1570555.00      6915088.00
      1569930.02      6915213.00
#Sta/Elev= 30
  3704.1 1685.43  3862.7 1683.67  3903.6 1686.53  4005.9 1689.95  4057.1 1687.23
  4343.5 1683.85  4374.2 1682.24  4394.6 1682.25  4412.8 1684.58  4417.9 1682.31
  4445.8 1685.15  4568.6 1677.14  4722.0 1677.41  4783.4 1675.07  4926.6 1676.15
  4939.6 1678.56  4977.8 1677.63  4983.8 1675.07  4984.3 1674.07  5016.2 1675.07
  5018.6 1676.98  5039.0 1675.43  5059.4 1677.99  5100.2 1676.52  5161.4 1677.44
  5202.2 1684.68  5263.4 1678.81  5324.6 1676.65  5569.3 1678.49  5645.8 1677.57
#Mann=3,-1,0
  3704.1    0.05       0  4983.8    0.05       0  5016.2    0.05       0
Bank Sta=4983.8,5016.2
Exp/Cntr=0.3,0.1

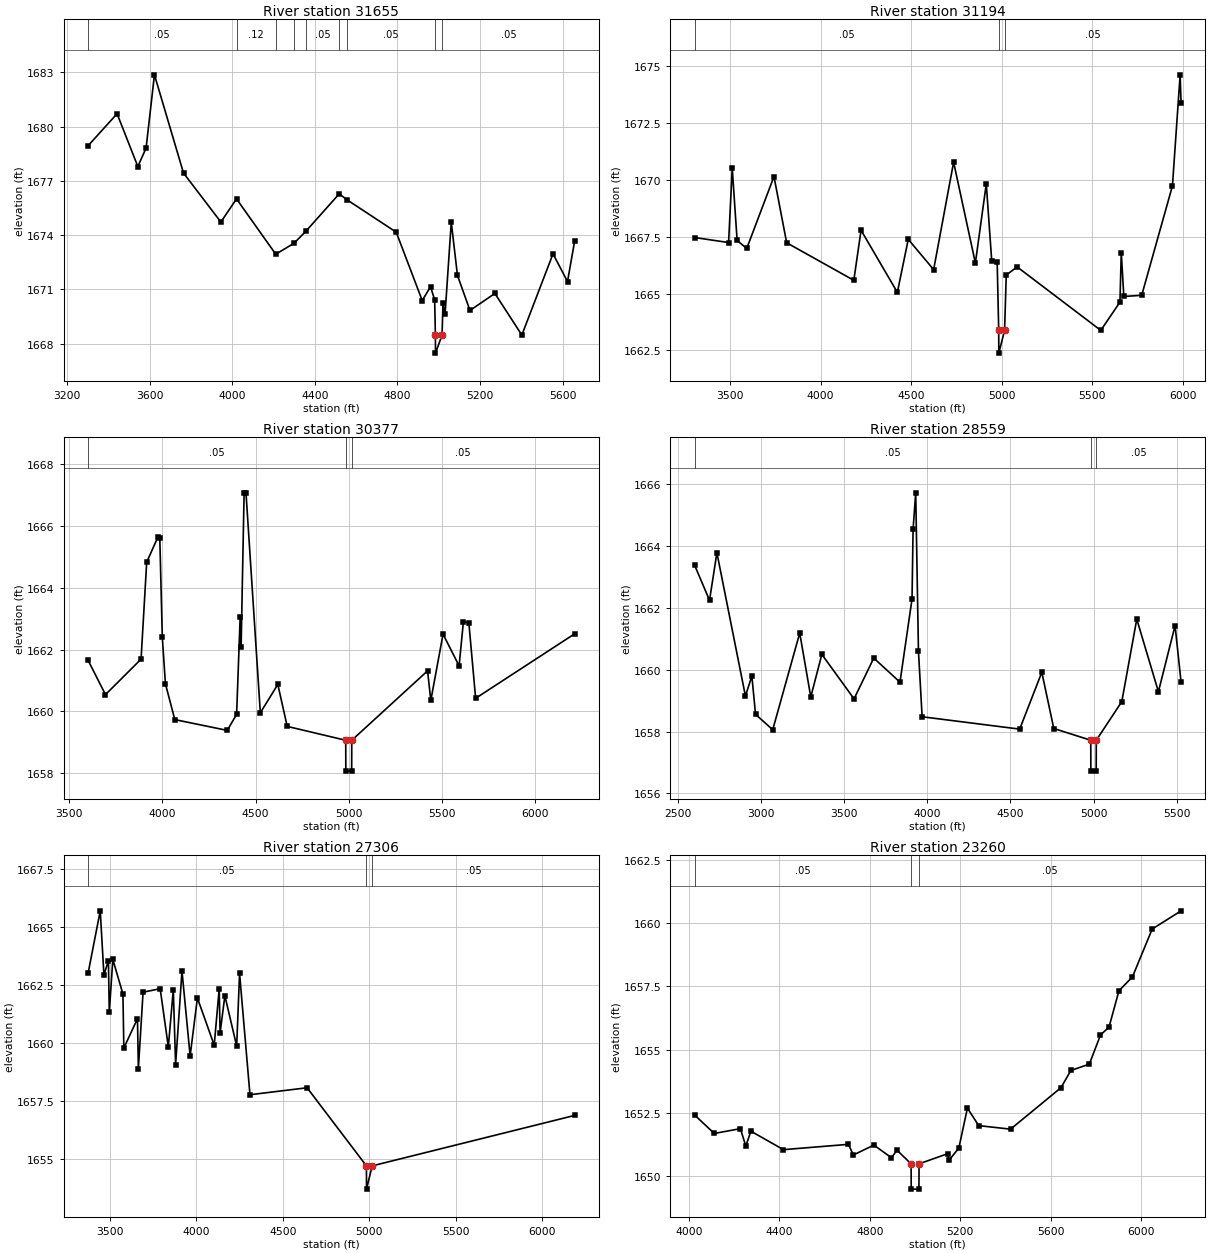
Type RM Length L Ch R = 1,31655,461,461,461
BEGIN DESCRIPTION:
Mapping XS 57e21dbf
END DESCRIPTION:
XS GIS Cut Line= 2
      1572244.52      6914454.60      1569900.81      6914688.97
#Sta/Elev= 30
  3302.5 1678.95  3442.7 1680.72  3543.2 1677.80  3583.2 1678.82  3623.6 1682.87
  3764.3 1677.44  3945.2 1674.73  4020.9 1676.01  4210.9 1672.95  4298.6 1673.55
  4356.0 1674.21  4518.3 1676.29  4554.5 1675.97  4794.2 1674.17  4920.0 1670.39
  4960.2 1671.15  4980.3 1670.43  4983.8 1668.48  4984.3 1667.48  5016.2 1668.48
  5020.5 1670.24  5030.6 1669.63  5060.7 1674.72  5090.6 1671.78  5151.2 1669.84
  5271.8 1670.78  5402.4 1668.48  5553.2 1672.97  5623.5 1671.44  5657.9 1673.67
#Mann=9,-1,0
  3302.5    0.05       0  4020.9    0.12       0  4210.9    0.05       0
  4298.6    0.12       0  4356.0    0.05       0  4518.3    0.12       0
  4554.5    0.05       0  4983.8    0.05       0  5016.2    0.05       0
Bank Sta=4983.8,5016.2
Exp/Cntr=0.3,0.1

Type RM Length L Ch R = 1,31194,817,817,817
BEGIN DESCRIPTION:
Mapping XS fdac5165
END DESCRIPTION:
XS GIS Cut Line= 3
      1572192.46      6914116.06      1570013.62      6914272.31
      1569666.40      6914636.89
#Sta/Elev= 30
  3303.5 1667.46  3491.4 1667.24  3511.5 1670.51  3538.5 1667.33  3591.7 1666.98
  3742.1 1670.14  3812.3 1667.23  4183.2 1665.58  4223.3 1667.78  4423.8 1665.05
  4484.0 1667.38  4624.3 1666.05  4734.6 1670.77  4854.9 1666.34  4915.1 1669.82
  4945.2 1666.43  4975.2 1666.40  4983.8 1663.38  4984.3 1662.38  5016.2 1663.38
  5025.4 1665.81  5085.5 1666.17  5547.7 1663.38  5653.6 1664.62  5660.9 1666.79
  5675.1 1664.87  5773.8 1664.92  5943.6 1669.73  5986.1 1674.61  5991.4 1673.35
#Mann=3,-1,0
  3303.5    0.05       0  4983.8    0.05       0  5016.2    0.05       0
Bank Sta=4983.8,5016.2
Exp/Cntr=0.3,0.1

Type RM Length L Ch R = 1,30377,1818,1818,1818
BEGIN DESCRIPTION:
Mapping XS 2d33cc8e
END DESCRIPTION:
XS GIS Cut Line= 3
      1571697.68      6913395.57      1570326.12      6913525.78
      1569198.84      6914020.05
#Sta/Elev= 30
  3602.5 1661.65  3695.6 1660.54  3886.4 1661.69  3916.6 1664.83  3976.9 1665.65
  3986.9 1665.60  4000.3 1662.40  4017.0 1660.89  4067.3 1659.73  4348.5 1659.38
  4398.7 1659.90  4417.8 1663.06  4422.8 1662.07  4438.9 1667.08  4449.0 1667.08
  4525.9 1659.95  4619.7 1660.87  4670.0 1659.51  4983.8 1659.06  4984.3 1658.06
  5015.7 1658.06  5016.2 1659.06  5422.6 1661.31  5440.0 1660.35  5505.6 1662.50
  5591.7 1661.47  5614.7 1662.90  5643.9 1662.87  5680.3 1660.42  6211.1 1662.51
#Mann=3,-1,0
  3602.5    0.05       0  4983.8   0.035       0  5016.2    0.05       0
Bank Sta=4983.8,5016.2
Exp/Cntr=0.3,0.1

Type RM Length L Ch R = 1,28559,1253,1253,1253
BEGIN DESCRIPTION:
Mapping XS 43a1bc0c
END DESCRIPTION:
XS GIS Cut Line= 3
      1572192.46      6913412.94      1570109.11      6912336.54
      1569528.78      6912362.53
#Sta/Elev= 30
  2600.7 1663.39  2690.6 1662.25  2734.9 1663.79  2906.5 1659.15  2945.1 1659.80
  2967.3 1658.56  3070.6 1658.06  3233.1 1661.19  3299.5 1659.12  3366.0 1660.50
  3559.7 1659.06  3678.4 1660.38  3836.0 1659.60  3908.4 1662.29  3914.8 1664.55
  3930.6 1665.73  3947.1 1660.60  3969.2 1658.48  4556.0 1658.08  4688.9 1659.92
  4761.0 1658.10  4983.4 1657.72  4983.9 1656.72  5016.1 1656.72  5016.6 1657.72
  5170.0 1658.97  5260.1 1661.64  5390.2 1659.29  5490.3 1661.43  5526.6 1659.60
#Mann=3,-1,0
  2600.7    0.05       0  4983.4   0.035       0  5016.6    0.05       0
Bank Sta=4983.4,5016.6
Exp/Cntr=0.3,0.1

Type RM Length L Ch R = 1,27306,4046,4046,4046
BEGIN DESCRIPTION:
Mapping XS 5ed40f35
END DESCRIPTION:
XS GIS Cut Line= 4
      1571072.66      6912596.93      1571272.30      6911763.63
      1570629.94      6911494.53      1569371.23      6911537.93
#Sta/Elev= 30
  3374.3 1663.01  3444.4 1665.69  3465.7 1662.93  3491.6 1663.55  3496.7 1661.34
  3517.2 1663.60  3575.6 1662.11  3580.8 1659.79  3659.7 1661.05  3664.8 1658.89
  3692.0 1662.19  3790.9 1662.34  3838.0 1659.84  3866.8 1662.29  3880.1 1659.08
  3917.0 1663.10  3964.1 1659.45  4006.2 1661.94  4103.3 1659.91  4132.2 1662.34
  4137.4 1660.44  4165.0 1662.04  4233.2 1659.87  4249.9 1663.00  4310.0 1657.78
  4640.3 1658.08  4983.4 1654.72  4983.9 1653.72  5016.6 1654.72  6187.1 1656.89
#Mann=3,-1,0
  3374.3    0.05       0  4983.4   0.035       0  5016.6    0.05       0
Bank Sta=4983.4,5016.6
Exp/Cntr=0.3,0.1

Type RM Length L Ch R = 1,23260,1180,1180,1180
BEGIN DESCRIPTION:
Mapping XS 566303c7
END DESCRIPTION:
XS GIS Cut Line= 3
      1573025.79      6909619.54      1572123.00      6909254.95
      1571089.99      6908690.70
#Sta/Elev= 30
  4025.3 1652.42  4112.4 1651.69  4227.7 1651.88  4251.8 1651.19  4274.2 1651.78
  4418.2 1651.05  4705.3 1651.26  4727.2 1650.84  4818.0 1651.23  4895.8 1650.73
  4920.0 1651.03  4982.4 1650.49  4982.9 1649.49  5017.1 1649.49  5017.6 1650.49
  5144.1 1650.89  5149.8 1650.63  5193.4 1651.11  5231.4 1652.69  5281.5 1652.00
  5422.1 1651.86  5645.1 1653.50  5688.7 1654.18  5770.3 1654.43  5819.7 1655.58
  5857.6 1655.90  5901.3 1657.33  5961.0 1657.88  6048.3 1659.77  6176.0 1660.49
#Mann=3,-1,0
  4025.3    0.05       0  4982.4   0.035       0  5017.6    0.05       0
Bank Sta=4982.4,5017.6
Exp/Cntr=0.3,0.1

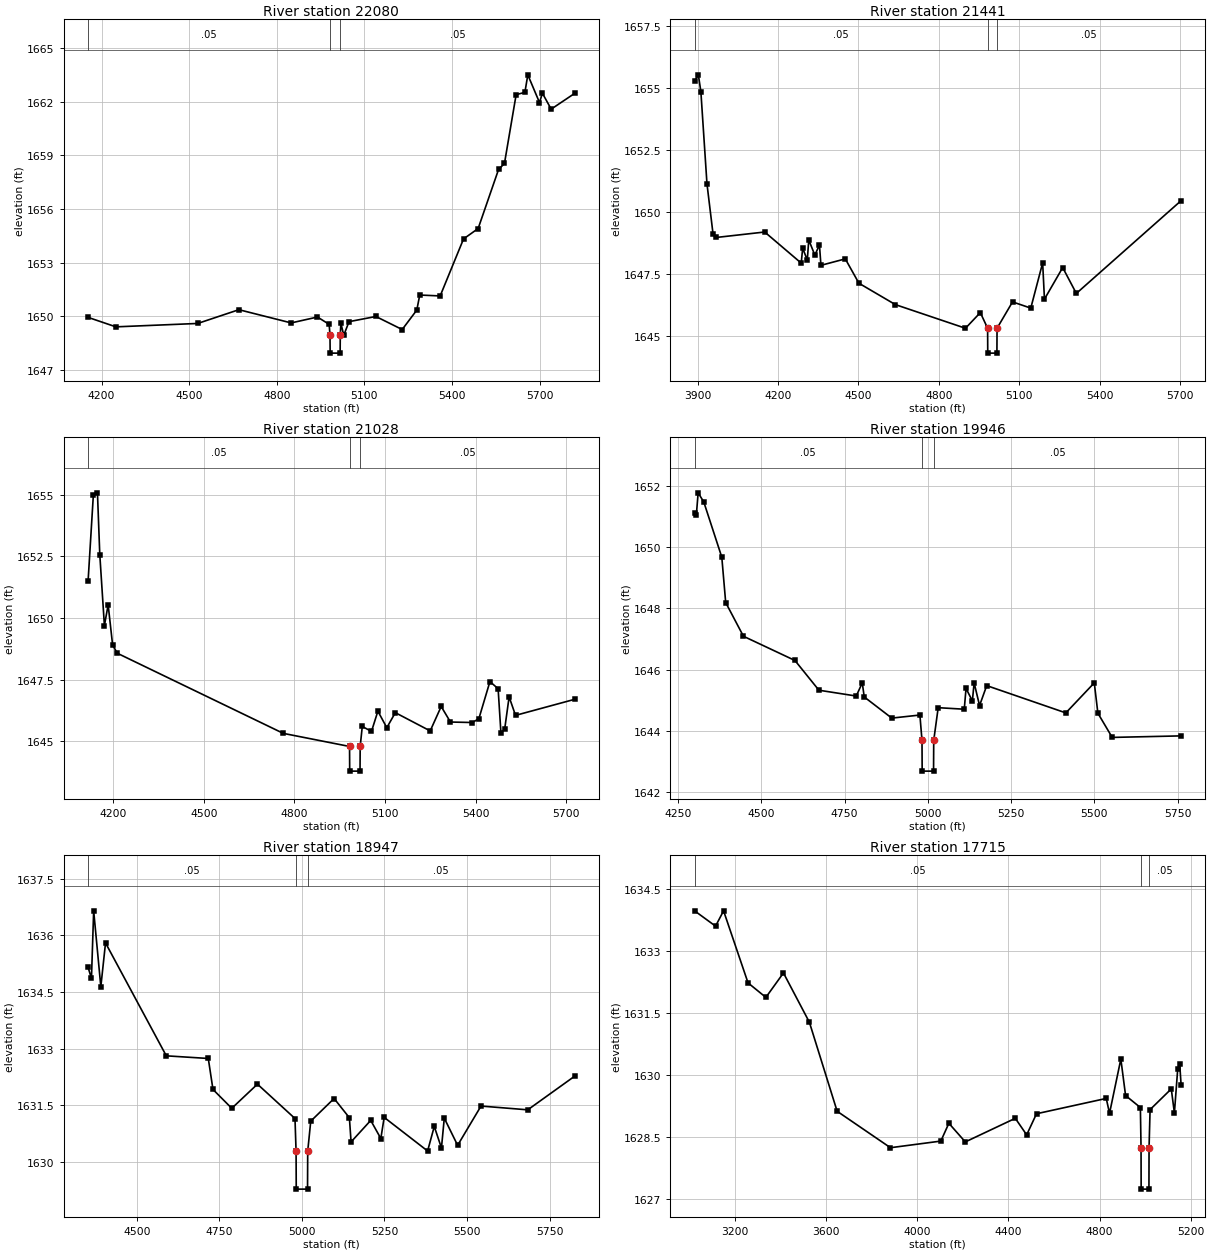
Type RM Length L Ch R = 1,22080,639,639,639
BEGIN DESCRIPTION:
Mapping XS 2dc2668d
END DESCRIPTION:
XS GIS Cut Line= 2
      1573260.17      6908456.34      1571594.73      6908412.97
#Sta/Elev= 30
  4154.1 1649.94  4249.3 1649.41  4529.4 1649.60  4670.4 1650.37  4849.5 1649.63
  4939.5 1649.96  4979.5 1649.55  4982.4 1648.94  4982.9 1647.94  5017.1 1647.94
  5017.6 1648.94  5019.6 1649.61  5029.6 1648.94  5047.5 1649.70  5139.6 1649.99
  5229.6 1649.26  5279.7 1650.35  5289.7 1651.19  5359.7 1651.14  5439.7 1654.33
  5489.7 1654.91  5559.7 1658.22  5579.8 1658.55  5619.8 1662.40  5649.8 1662.53
  5659.8 1663.51  5699.8 1661.96  5709.8 1662.48  5739.8 1661.59  5820.1 1662.47
#Mann=3,-1,0
  4154.1    0.05       0  4982.4    0.05       0  5017.6    0.05       0
Bank Sta=4982.4,5017.6
Exp/Cntr=0.3,0.1

Type RM Length L Ch R = 1,21441,413,413,413
BEGIN DESCRIPTION:
Mapping XS 903bc4d3
END DESCRIPTION:
XS GIS Cut Line= 2
      1573407.70      6908334.80      1571768.55      6907554.25
#Sta/Elev= 30
  3888.9 1655.27  3903.0 1655.52  3912.4 1654.84  3935.1 1651.14  3957.8 1649.12
  3969.4 1648.98  4150.6 1649.20  4286.8 1647.95  4292.3 1648.55  4309.5 1648.07
  4315.0 1648.88  4337.7 1648.27  4354.9 1648.68  4360.4 1647.86  4451.3 1648.12
  4502.2 1647.14  4638.4 1646.28  4899.8 1645.33  4955.2 1645.96  4982.4 1645.33
  4982.9 1644.33  5017.1 1644.33  5017.6 1645.33  5075.4 1646.39  5143.5 1646.14
  5187.8 1647.96  5194.5 1646.50  5262.6 1647.77  5313.5 1646.73  5704.4 1650.46
#Mann=3,-1,0
  3888.9    0.05       0  4982.4    0.05       0  5017.6    0.05       0
Bank Sta=4982.4,5017.6
Exp/Cntr=0.3,0.1

Type RM Length L Ch R = 1,21028,1082,1082,1082
BEGIN DESCRIPTION:
Mapping XS f37fb1d7
END DESCRIPTION:
XS GIS Cut Line= 2
      1573451.12      6908204.60      1572089.18      6907345.79
#Sta/Elev= 30
  4117.2 1651.51  4134.6 1655.00  4148.1 1655.07  4155.8 1652.57  4171.1 1649.69
  4183.5 1650.53  4198.2 1648.91  4213.5 1648.57  4763.2 1645.32  4982.4 1644.79
  4982.9 1643.79  5017.1 1643.79  5017.6 1644.79  5024.5 1645.60  5055.0 1645.40
  5076.2 1646.22  5105.7 1645.55  5133.9 1646.16  5249.3 1645.42  5285.7 1646.41
  5316.3 1645.78  5389.3 1645.76  5410.5 1645.92  5447.0 1647.42  5474.1 1647.13
  5483.4 1645.34  5495.8 1645.49  5510.5 1646.80  5531.7 1646.05  5727.3 1646.70
#Mann=3,-1,0
  4117.2    0.05       0  4982.4   0.035       0  5017.6    0.05       0
Bank Sta=4982.4,5017.6
Exp/Cntr=0.3,0.1

Type RM Length L Ch R = 1,19946,999,999,999
BEGIN DESCRIPTION:
Mapping XS 89181e70
END DESCRIPTION:
XS GIS Cut Line= 3
      1573513.76      6907993.59      1573253.32      6907359.87
      1572532.83      6907073.41
#Sta/Elev= 30
  4299.7 1651.11  4305.0 1651.05  4310.4 1651.77  4327.4 1651.47  4381.4 1649.67
  4393.1 1648.19  4446.4 1647.09  4601.0 1646.30  4672.9 1645.33  4785.0 1645.14
  4803.1 1645.57  4809.0 1645.11  4891.7 1644.42  4976.1 1644.52  4982.4 1643.69
  4982.9 1642.69  5017.1 1642.69  5017.6 1643.69  5031.0 1644.76  5109.3 1644.71
  5114.6 1645.39  5133.6 1644.98  5138.9 1645.57  5155.2 1644.83  5176.7 1645.48
  5414.2 1644.59  5499.6 1645.57  5510.4 1644.58  5553.4 1643.79  5760.2 1643.84
#Mann=3,-1,0
  4299.7    0.05       0  4982.4   0.035       0  5017.6    0.05       0
Bank Sta=4982.4,5017.6
Exp/Cntr=0.3,0.1

Type RM Length L Ch R = 1,18947,1232,1232,1232
BEGIN DESCRIPTION:
Mapping XS e253061b
END DESCRIPTION:
XS GIS Cut Line= 3
      1574086.62      6906960.54      1573609.23      6906535.22
      1572784.61      6906413.70
#Sta/Elev= 30
  4352.8 1635.15  4362.9 1634.86  4369.6 1636.65  4391.3 1634.64  4405.5 1635.80
  4589.5 1632.81  4716.6 1632.74  4730.8 1631.92  4787.7 1631.42  4865.4 1632.06
  4979.1 1631.15  4982.4 1630.28  4982.9 1629.28  5017.1 1629.28  5017.6 1630.28
  5026.8 1631.08  5097.5 1631.68  5143.8 1631.17  5148.9 1630.53  5208.4 1631.10
  5239.0 1630.62  5249.1 1631.18  5380.6 1630.29  5400.8 1630.94  5422.5 1630.37
  5431.1 1631.16  5471.5 1630.44  5542.3 1631.48  5683.8 1631.38  5825.7 1632.27
#Mann=3,-1,0
  4352.8    0.05       0  4982.4   0.035       0  5017.6    0.05       0
Bank Sta=4982.4,5017.6
Exp/Cntr=0.3,0.1

Type RM Length L Ch R = 1,17715,1298,1298,1298
BEGIN DESCRIPTION:
Mapping XS 2e3c7688
END DESCRIPTION:
XS GIS Cut Line= 3
      1575247.99      6907024.03      1574043.25      6905493.55
      1573890.08      6905382.93
#Sta/Elev= 30
  3021.6 1633.97  3113.7 1633.60  3148.9 1633.97  3256.4 1632.23  3334.7 1631.88
  3411.9 1632.47  3525.8 1631.28  3647.7 1629.13  3881.9 1628.25  4103.1 1628.41
  4138.4 1628.84  4210.6 1628.39  4430.2 1628.96  4480.1 1628.56  4523.3 1629.07
  4829.6 1629.44  4844.0 1629.08  4893.7 1630.39  4914.5 1629.51  4979.5 1629.22
  4982.4 1628.25  4982.9 1627.25  5017.1 1627.25  5017.6 1628.25  5022.1 1629.17
  5115.2 1629.67  5128.9 1629.09  5143.6 1630.16  5152.1 1630.28  5158.3 1629.77
#Mann=3,-1,0
  3021.6    0.05       0  4982.4    0.03       0  5017.6    0.05       0
Bank Sta=4982.4,5017.6
Exp/Cntr=0.3,0.1

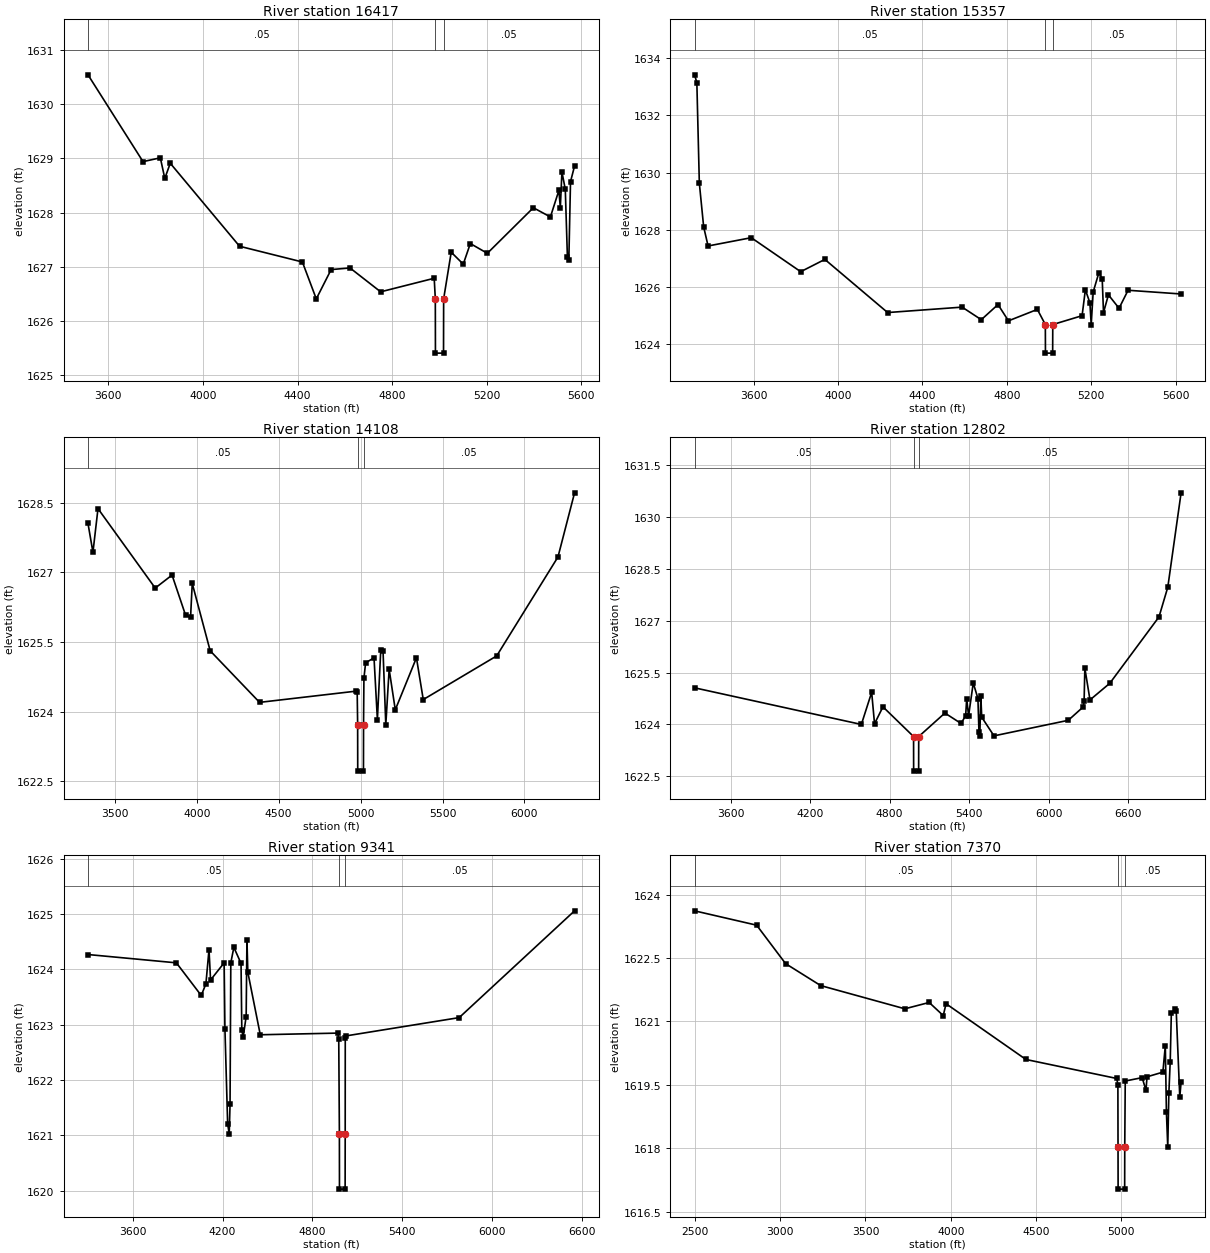
Type RM Length L Ch R = 1,16417,1060,1060,1060
BEGIN DESCRIPTION:
Mapping XS a61d46ea
END DESCRIPTION:
XS GIS Cut Line= 3
      1575586.54      6906720.24      1575163.04      6905345.98
      1574815.82      6904833.83
#Sta/Elev= 30
  3514.2 1630.54  3746.8 1628.94  3820.0 1629.01  3838.9 1628.63  3861.9 1628.91
  4154.9 1627.38  4420.5 1627.09  4479.2 1626.41  4542.0 1626.95  4621.8 1626.98
  4751.3 1626.54  4977.7 1626.79  4982.4 1626.41  4982.9 1625.41  5017.1 1625.41
  5017.6 1626.41  5049.6 1627.27  5100.5 1627.05  5130.4 1627.43  5202.3 1627.25
  5396.8 1628.09  5468.9 1627.92  5504.8 1628.41  5510.8 1628.09  5517.6 1628.75
  5531.8 1628.43  5540.7 1627.19  5546.8 1627.13  5553.9 1628.57  5571.0 1628.86
#Mann=3,-1,0
  3514.2    0.05       0  4982.4    0.05       0  5017.6    0.05       0
Bank Sta=4982.4,5017.6
Exp/Cntr=0.3,0.1

Type RM Length L Ch R = 1,15357,1249,1249,1249
BEGIN DESCRIPTION:
Mapping XS a30eadf0
END DESCRIPTION:
XS GIS Cut Line= 3
      1576463.27      6906720.21      1576102.22      6905145.38
      1575748.33      6904552.10
#Sta/Elev= 30
  3319.4 1633.42  3330.4 1633.15  3342.2 1629.63  3362.7 1628.10  3383.6 1627.43
  3588.4 1627.72  3822.8 1626.53  3937.2 1626.96  4234.8 1625.10  4587.9 1625.29
  4678.8 1624.85  4758.0 1625.38  4807.5 1624.81  4944.5 1625.21  4982.4 1624.68
  4982.9 1623.68  5017.1 1623.68  5017.6 1624.68  5156.6 1624.99  5172.2 1625.90
  5193.6 1625.44  5199.8 1624.68  5209.2 1625.82  5236.4 1626.50  5252.0 1626.28
  5258.1 1625.10  5281.4 1625.72  5331.8 1625.25  5374.6 1625.88  5625.9 1625.75
#Mann=3,-1,0
  3319.4    0.05       0  4982.4    0.03       0  5017.6    0.05       0
Bank Sta=4982.4,5017.6
Exp/Cntr=0.3,0.1

Type RM Length L Ch R = 1,14108,1306,1306,1306
BEGIN DESCRIPTION:
Mapping XS d71ba999
END DESCRIPTION:
XS GIS Cut Line= 3
      1576619.51      6906697.39      1577044.24      6904885.15
      1576732.69      6903822.00
#Sta/Elev= 30
  3336.5 1628.05  3366.7 1627.43  3397.5 1628.37  3746.7 1626.66  3849.4 1626.94
  3931.6 1626.08  3962.4 1626.03  3972.7 1626.76  4082.1 1625.31  4383.5 1624.20
  4969.0 1624.44  4979.2 1624.43  4982.0 1623.72  4982.5 1622.72  5017.5 1622.72
  5018.0 1623.72  5020.3 1624.72  5030.6 1625.05  5081.9 1625.16  5102.5 1623.83
  5123.0 1625.32  5136.9 1625.31  5153.8 1623.72  5174.3 1624.91  5211.7 1624.04
  5340.8 1625.16  5382.4 1624.26  5830.5 1625.20  6204.5 1627.33  6305.7 1628.71
#Mann=3,-1,0
  3336.5    0.05       0  4982.0    0.03       0  5018.0    0.05       0
Bank Sta=4982,5018
Exp/Cntr=0.3,0.1

Type RM Length L Ch R = 1,12802,3461,3461,3461
BEGIN DESCRIPTION:
Mapping XS 77334249
END DESCRIPTION:
XS GIS Cut Line= 4
      1579136.85      6906454.28      1577904.24      6905325.83
      1577171.80      6904432.86      1576784.70      6903682.50
#Sta/Elev= 30
  3328.2 1625.06  4586.8 1624.00  4664.5 1624.93  4686.1 1624.02  4749.6 1624.51
  4980.6 1623.65  4981.1 1622.65  5018.9 1622.65  5019.4 1623.65  5216.9 1624.33
  5338.2 1624.03  5373.4 1624.25  5381.3 1624.75  5395.6 1624.25  5430.8 1625.20
  5466.0 1624.75  5473.8 1623.79  5480.3 1623.68  5488.0 1624.81  5494.7 1624.21
  5587.2 1623.67  6147.7 1624.12  6261.0 1624.51  6267.0 1624.68  6272.6 1625.63
  6311.3 1624.71  6460.7 1625.19  6831.8 1627.11  6898.3 1627.97  6998.6 1630.70
#Mann=3,-1,0
  3328.2    0.05       0  4980.6   0.035       0  5019.4    0.05       0
Bank Sta=4980.6,5019.4
Exp/Cntr=0.3,0.1

Type RM Length L Ch R = 1,9341,1971,1971,1971
BEGIN DESCRIPTION:
Mapping XS 26ecd367
END DESCRIPTION:
XS GIS Cut Line= 3
      1580004.94      6905557.03      1579562.23      6903968.49
      1578294.87      6902987.58
#Sta/Elev= 30
  3300.5 1624.27  3891.2 1624.12  4057.3 1623.53  4088.5 1623.74  4109.2 1624.36
  4119.6 1623.81  4210.4 1624.12  4215.6 1622.93  4233.8 1621.21  4244.2 1621.03
  4249.8 1621.56  4254.9 1624.12  4275.3 1624.40  4323.3 1624.11  4328.5 1622.90
  4337.6 1622.78  4357.5 1623.15  4362.7 1624.54  4368.7 1623.95  4451.8 1622.82
  4970.0 1622.85  4976.3 1622.74  4980.6 1621.03  4981.1 1620.03  5018.9 1620.03
  5019.4 1621.03  5019.8 1622.77  5026.1 1622.80  5781.2 1623.13  6552.2 1625.06
#Mann=3,-1,0
  3300.5    0.05       0  4980.6   0.035       0  5019.4    0.05       0
Bank Sta=4980.6,5019.4
Exp/Cntr=0.3,0.1

Type RM Length L Ch R = 1,7370,1261,1261,1261
BEGIN DESCRIPTION:
Mapping XS 39795053
END DESCRIPTION:
XS GIS Cut Line= 3
      1580300.07      6905131.71      1580777.50      6903233.82
      1580213.26      6902539.37
#Sta/Elev= 30
  2498.1 1623.62  2862.2 1623.28  3031.8 1622.37  3237.4 1621.85  3730.8 1621.30
  3873.4 1621.45  3955.9 1621.14  3972.4 1621.42  4440.5 1620.10  4973.0 1619.65
  4979.5 1619.50  4980.3 1618.03  4980.8 1617.03  5019.2 1617.03  5019.7 1618.03
  5022.6 1619.59  5121.7 1619.67  5144.0 1619.37  5150.4 1619.69  5243.1 1619.80
  5257.5 1620.43  5263.9 1618.85  5271.8 1618.03  5278.3 1619.31  5286.2 1620.05
  5292.7 1621.19  5313.5 1621.29  5321.4 1621.25  5342.2 1619.21  5349.9 1619.56
#Mann=3,-1,0
  2498.1    0.05       0  4980.3   0.035       0  5019.7    0.05       0
Bank Sta=4980.3,5019.7
Exp/Cntr=0.3,0.1