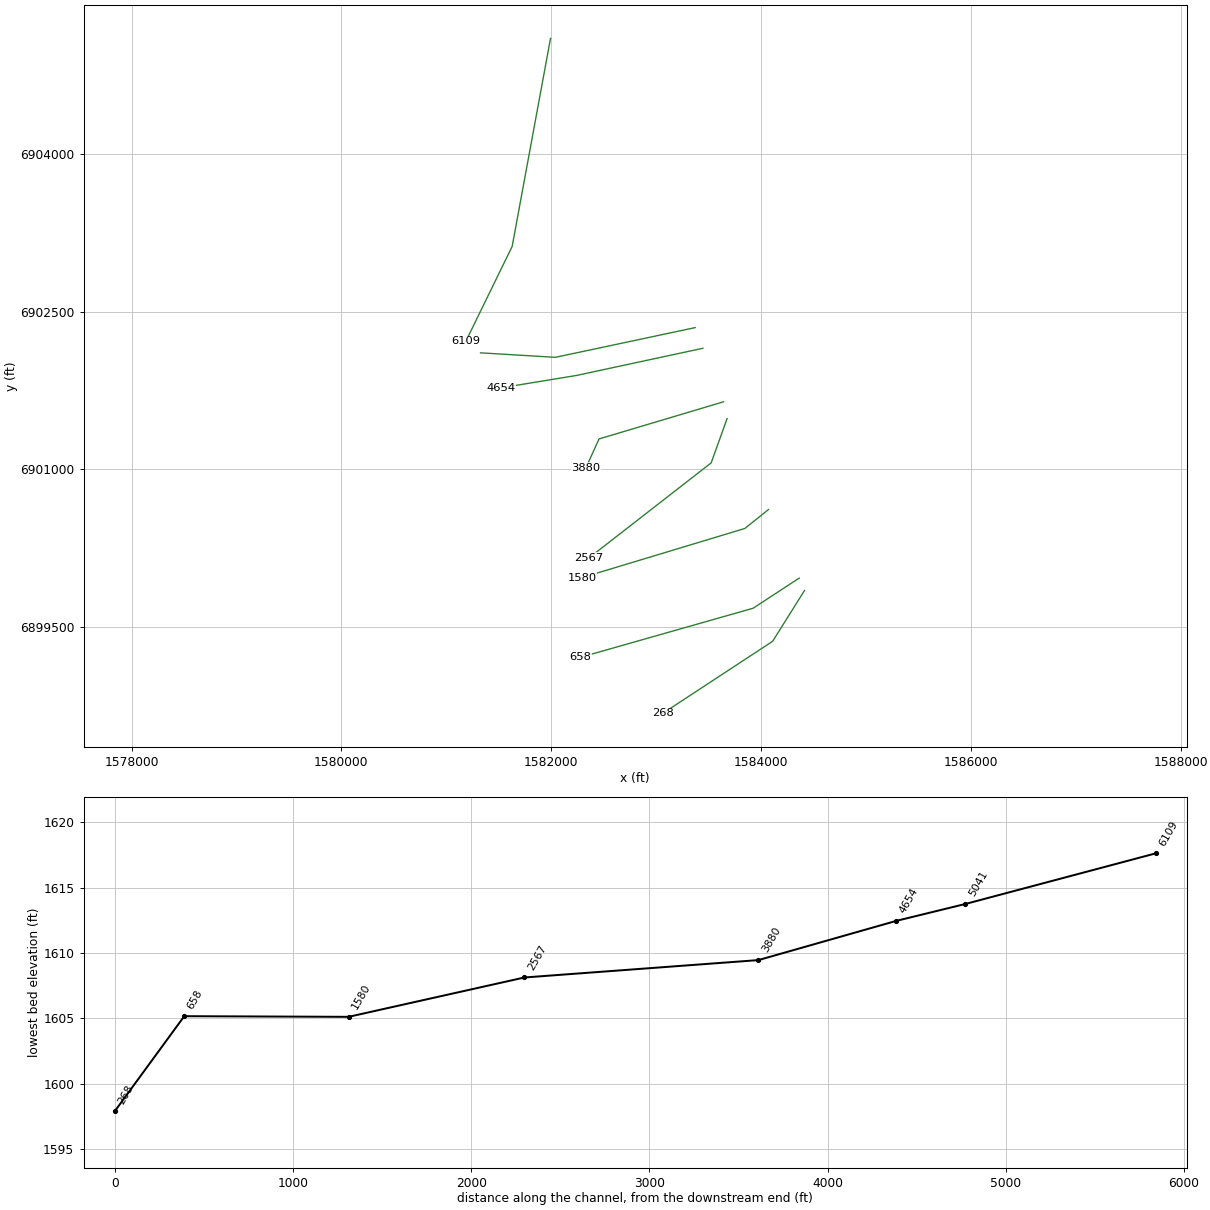
HEC-RAS study Deadman 17.prj: Deadman 17 Base Level Engineering

--- Deadman 17.g01 (geometry) --- (continued)

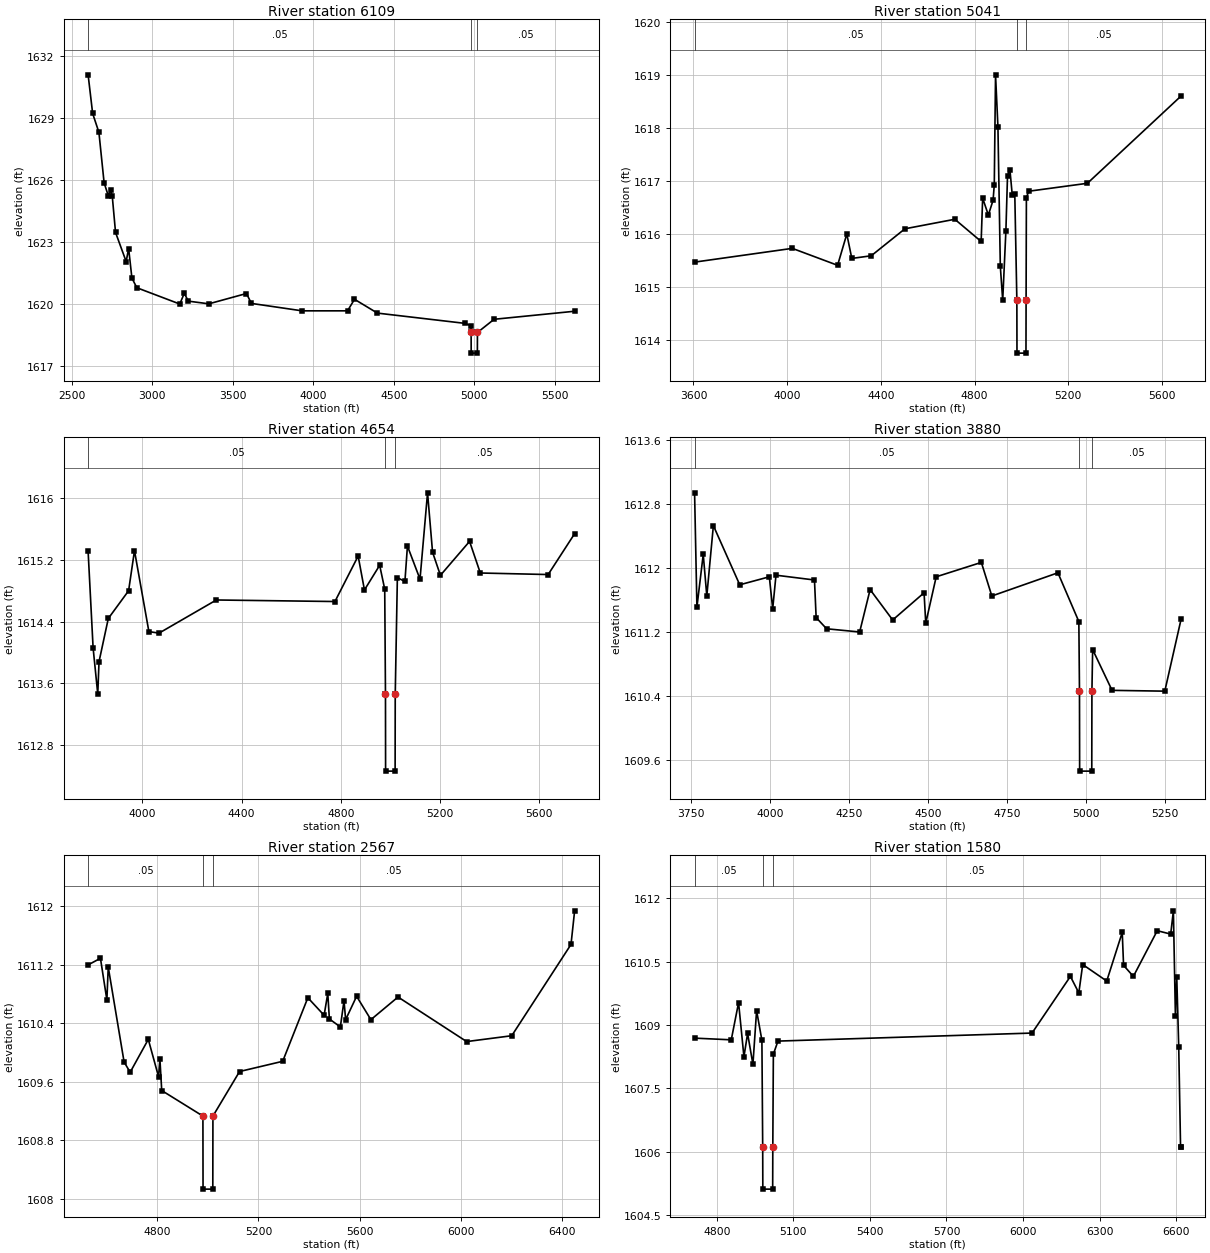
Type RM Length L Ch R = 1,6109,1068,1068,1068
BEGIN DESCRIPTION:
Mapping XS dbab33a7
END DESCRIPTION:
XS GIS Cut Line= 3
      1581992.79      6905105.62      1581627.15      6903122.55
      1581185.51      6902218.23
#Sta/Elev= 30
  2600.6 1631.11  2628.7 1629.24  2667.7 1628.32  2699.9 1625.88  2725.8 1625.25
  2740.5 1625.53  2750.7 1625.22  2771.0 1623.47  2836.9 1622.06  2852.4 1622.69
  2872.7 1621.26  2903.2 1620.79  3170.1 1620.00  3198.1 1620.52  3223.1 1620.14
  3350.7 1620.01  3584.5 1620.51  3615.0 1620.03  3930.3 1619.67  4212.6 1619.67
  4255.7 1620.23  4398.0 1619.56  4944.9 1619.06  4979.5 1618.94  4980.3 1618.62
  4980.8 1617.62  5019.2 1617.62  5019.7 1618.62  5123.0 1619.26  5623.5 1619.65
#Mann=3,-1,0
  2600.6    0.05       0  4980.3   0.035       0  5019.7    0.05       0
Bank Sta=4980.3,5019.7
Exp/Cntr=0.3,0.1

Type RM Length L Ch R = 1,5041,387,387,387
BEGIN DESCRIPTION:
Deadman 17 4.0
END DESCRIPTION:
XS GIS Cut Line= 3
      1583371.47      6902348.98      1582038.94      6902065.69
      1581325.93      6902108.47
#Sta/Elev= 30
  3604.7 1615.47  4021.8 1615.73  4215.1 1615.41  4254.4 1616.00  4275.8 1615.54
  4358.8 1615.59  4502.5 1616.10  4715.5 1616.28  4827.9 1615.86  4834.3 1616.68
  4858.6 1616.36  4878.8 1616.64  4883.9 1616.93  4889.3 1619.01  4899.5 1618.03
  4909.7 1615.39  4919.9 1614.75  4933.5 1616.06  4940.4 1617.10  4950.6 1617.22
  4960.8 1616.73  4971.5 1616.75  4980.3 1614.75  4980.8 1613.75  5019.2 1613.75
  5019.7 1614.75  5021.0 1616.69  5031.1 1616.81  5281.5 1616.96  5681.3 1618.61
#Mann=3,-1,0
  3604.7    0.05       0  4980.3    0.03       0  5019.7    0.05       0
Bank Sta=4980.3,5019.7
Exp/Cntr=0.3,0.1

Type RM Length L Ch R = 1,4654,774,774,774
BEGIN DESCRIPTION:
Deadman 17 3.0
END DESCRIPTION:
XS GIS Cut Line= 3
      1583444.63      6902151.91      1582239.76      6901892.92
      1581519.58      6901774.77
#Sta/Elev= 30
  3781.0 1615.31  3801.1 1614.06  3819.9 1613.46  3825.0 1613.88  3862.4 1614.44
  3944.3 1614.80  3968.0 1615.32  4026.1 1614.27  4067.0 1614.25  4298.2 1614.68
  4776.5 1614.66  4870.1 1615.25  4895.5 1614.81  4956.9 1615.13  4977.3 1614.82
  4980.3 1613.46  4980.8 1612.46  5019.2 1612.46  5019.7 1613.46  5028.3 1614.97
  5058.7 1614.92  5068.9 1615.38  5119.6 1614.95  5150.0 1616.07  5170.2 1615.30
  5201.9 1615.00  5319.5 1615.44  5362.8 1615.03  5636.4 1615.01  5743.2 1615.54
#Mann=3,-1,0
  3781.0    0.05       0  4980.3    0.03       0  5019.7    0.05       0
Bank Sta=4980.3,5019.7
Exp/Cntr=0.3,0.1

Type RM Length L Ch R = 1,3880,1313,1313,1313
BEGIN DESCRIPTION:
Deadman 17 2.0
END DESCRIPTION:
XS GIS Cut Line= 3
      1583642.06      6901642.09      1582455.00      6901288.00
      1582330.01      6901013.02
#Sta/Elev= 30
  3761.3 1612.94  3768.7 1611.51  3788.7 1612.17  3800.0 1611.65  3820.8 1612.53
  3904.3 1611.79  3998.0 1611.89  4008.7 1611.49  4019.1 1611.91  4141.0 1611.85
  4146.3 1611.38  4179.4 1611.24  4284.1 1611.20  4317.2 1611.73  4388.7 1611.35
  4488.1 1611.69  4493.4 1611.31  4526.5 1611.89  4669.5 1612.07  4702.7 1611.65
  4912.0 1611.94  4978.3 1611.33  4980.3 1610.46  4980.8 1609.46  5019.2 1609.46
  5019.7 1610.46  5022.0 1610.98  5083.5 1610.47  5250.5 1610.46  5302.1 1611.36
#Mann=3,-1,0
  3761.3    0.05       0  4980.3   0.035       0  5019.7    0.05       0
Bank Sta=4980.3,5019.7
Exp/Cntr=0.3,0.1

Type RM Length L Ch R = 1,2567,987,987,987
BEGIN DESCRIPTION:
Mapping XS fe46575e
END DESCRIPTION:
XS GIS Cut Line= 3
      1583675.48      6901481.92      1583523.46      6901059.64
      1582359.01      6900153.96
#Sta/Elev= 30
  4526.2 1611.20  4575.0 1611.29  4600.4 1610.72  4605.8 1611.17  4668.5 1609.87
  4692.5 1609.73  4764.2 1610.18  4804.7 1609.67  4810.1 1609.91  4817.3 1609.48
  4980.2 1609.13  4980.7 1608.13  5019.3 1608.13  5019.8 1609.13  5125.1 1609.74
  5295.7 1609.88  5395.2 1610.75  5459.5 1610.51  5474.0 1610.81  5480.3 1610.46
  5523.7 1610.35  5538.2 1610.71  5544.6 1610.45  5588.0 1610.77  5644.5 1610.45
  5751.8 1610.76  6023.2 1610.15  6201.5 1610.23  6435.9 1611.48  6450.2 1611.94
#Mann=3,-1,0
  4526.2    0.05       0  4980.2    0.03       0  5019.8    0.05       0
Bank Sta=4980.2,5019.8
Exp/Cntr=0.3,0.1

Type RM Length L Ch R = 1,1580,922,922,922
BEGIN DESCRIPTION:
Mapping XS 6070450e
END DESCRIPTION:
XS GIS Cut Line= 3
      1584069.57      6900614.83      1583844.39      6900434.68
      1582296.05      6899967.37
#Sta/Elev= 30
  4713.4 1608.69  4857.1 1608.65  4885.7 1609.53  4906.7 1608.25  4921.1 1608.80
  4941.9 1608.07  4956.3 1609.34  4977.1 1608.64  4980.2 1606.12  4980.7 1605.12
  5019.3 1605.12  5019.8 1606.12  5022.0 1608.31  5040.0 1608.62  6035.2 1608.81
  6185.5 1610.15  6218.5 1609.76  6233.7 1610.43  6327.8 1610.04  6388.6 1611.19
  6393.8 1610.41  6432.2 1610.15  6525.7 1611.23  6578.4 1611.15  6588.9 1611.70
  6596.8 1609.22  6602.1 1610.14  6609.8 1608.49  6617.0 1606.12  6619.1 1606.12
#Mann=3,-1,0
  4713.4    0.05       0  4980.2    0.03       0  5019.8    0.05       0
Bank Sta=4980.2,5019.8
Exp/Cntr=0.3,0.1

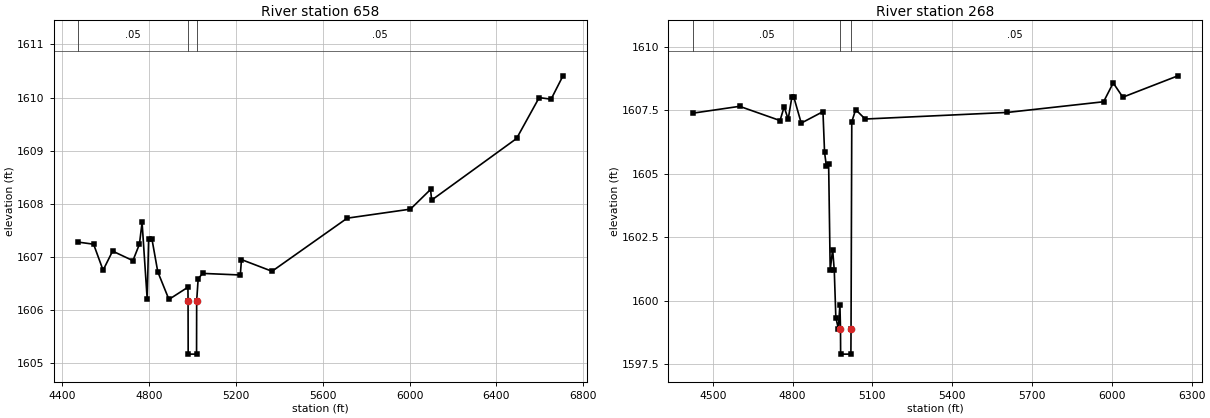
Type RM Length L Ch R = 1,658,390,390,390
BEGIN DESCRIPTION:
Mapping XS 32e4fdbd
END DESCRIPTION:
XS GIS Cut Line= 3
      1584362.41      6899961.77      1583923.21      6899674.60
      1582279.57      6899207.40
#Sta/Elev= 30
  4472.6 1607.28  4545.3 1607.24  4589.0 1606.75  4632.8 1607.11  4726.3 1606.93
  4756.3 1607.24  4768.5 1607.65  4792.1 1606.20  4798.7 1607.34  4813.8 1607.34
  4840.8 1606.72  4892.1 1606.20  4979.6 1606.43  4980.2 1606.17  4980.7 1605.17
  5019.3 1605.17  5019.8 1606.17  5026.7 1606.59  5047.5 1606.69  5220.8 1606.66
  5226.0 1606.95  5366.7 1606.73  5712.8 1607.73  6003.9 1607.90  6096.4 1608.27
  6101.6 1608.07  6492.5 1609.23  6596.5 1610.00  6651.4 1609.97  6706.1 1610.41
#Mann=3,-1,0
  4472.6    0.05       0  4980.2    0.03       0  5019.8    0.05       0
Bank Sta=4980.2,5019.8
Exp/Cntr=0.3,0.1

Type RM Length L Ch R = 1,268,0,0,0
BEGIN DESCRIPTION:
Deadman 17 1.0
END DESCRIPTION:
XS GIS Cut Line= 3
      1584413.02      6899843.47      1584109.01      6899359.30
      1583062.20      6898672.68
#Sta/Elev= 30
  4424.7 1607.38  4601.0 1607.65  4753.0 1607.09  4768.3 1607.63  4783.6 1607.14
  4797.2 1608.00  4804.8 1608.01  4832.6 1606.99  4914.3 1607.44  4920.3 1605.84
  4927.1 1605.30  4935.6 1605.39  4941.5 1601.21  4950.7 1602.01  4956.8 1601.20
  4962.7 1599.34  4972.1 1598.90  4978.0 1599.84  4980.2 1598.90  4980.7 1597.90
  5019.3 1597.90  5019.8 1598.90  5022.6 1607.04  5037.1 1607.52  5073.0 1607.15
  5607.4 1607.41  5969.1 1607.83  6005.2 1608.57  6041.4 1608.01  6248.3 1608.85
#Mann=3,-1,0
  4424.7    0.05       0  4980.2    0.03       0  5019.8    0.05       0
Bank Sta=4980.2,5019.8
Exp/Cntr=0.3,0.1

Chan Stop Cuts=-1