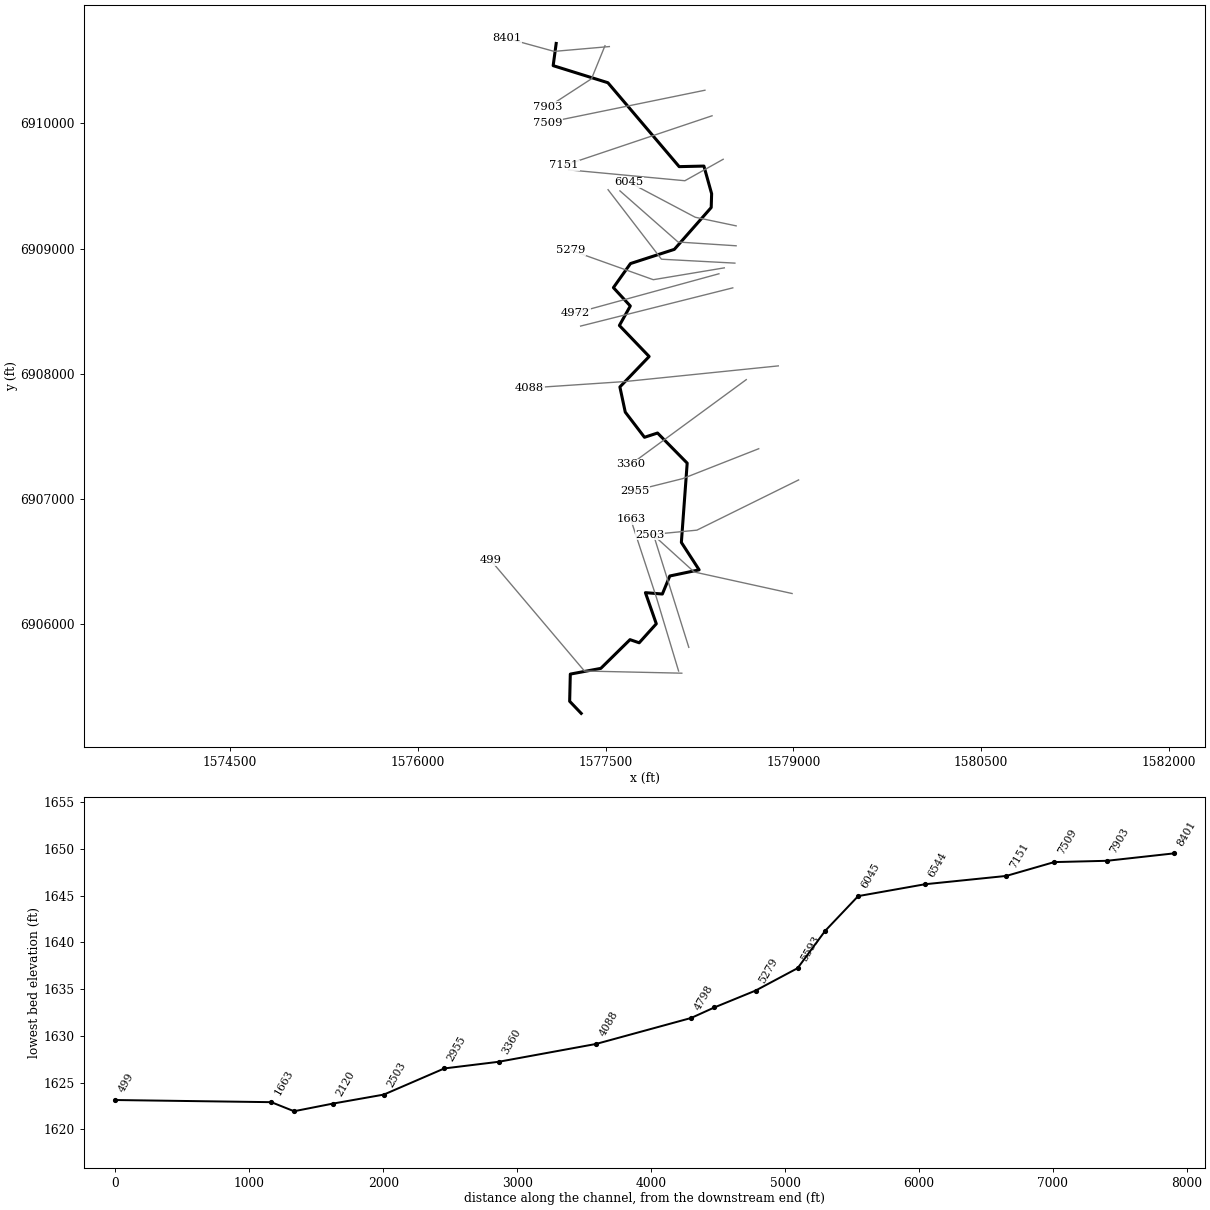
--- Deadman 18.prj (project) ---

Proj Title=Deadman 18 Base Level Engineering
Current Plan=p01
Default Exp/Contr=0.3,0.1
English Units
Geom File=g01
Flow File=f01
Plan File=p01
BEGIN DESCRIPTION:
Deadman 18
END DESCRIPTION:

--- Deadman 18.p01 (plan) ---

Plan Title=Multiple Run
Short Identifier=Multiple
Geom File=g01
Flow File=f01
Subcritical Flow
K Sum by GR= 0
Std Step Tol= 0.01
Critical Tol= 0.01
Num of Std Step Trials= 20
Max Error Tol= 0.3
Flow Tol Ratio= 0.001
Split Flow NTrial= 30
Split Flow Tol= 0.02
Split Flow Ratio= 0.02
Log Output Level= 0
Friction Slope Method= 1
Unsteady Friction Slope Method= 2
Unsteady Bridges Friction Slope Method= 1
Parabolic Critical Depth
Global Vel Dist=  1 , 1 , 1
Global Log Level= 0
CheckData=True
Encroach Param= -1, 0, 0, 0
BEGIN DESCRIPTION:
Multiple Run
END DESCRIPTION:

--- Deadman 18.f01 (steady flow) ---

Flow Title=Multiple
Number of Profiles=7
Profile Names=10-year,25-year,50-year,1pct_min,100-year,1pct_plu,500-year
River Rch & RM= Deadman 18,Reach-1,8401
     177     237     285     170     339     677     489
River Rch & RM= Deadman 18,Reach-1,2120
     272     373     455     276     551    1099     818
Boundary for River Rch & Prof#=Deadman 18,Reach-1,1
Up Type=0
Dn Type=3
Dn Slope=0.005
Boundary for River Rch & Prof#=Deadman 18,Reach-1,2
Up Type=0
Dn Type=3
Dn Slope=0.005
Boundary for River Rch & Prof#=Deadman 18,Reach-1,3
Up Type=0
Dn Type=3
Dn Slope=0.005
Boundary for River Rch & Prof#=Deadman 18,Reach-1,4
Up Type=0
Dn Type=3
Dn Slope=0.005
Boundary for River Rch & Prof#=Deadman 18,Reach-1,5
Up Type=0
Dn Type=3
Dn Slope=0.005
Boundary for River Rch & Prof#=Deadman 18,Reach-1,6
Up Type=0
Dn Type=3
Dn Slope=0.005
Boundary for River Rch & Prof#=Deadman 18,Reach-1,7
Up Type=0
Dn Type=3
Dn Slope=0.005

--- Deadman 18.g01 (geometry) ---

Geom Title=Existing Conditions

River Reach=Deadman 18,Reach-1
Reach XY= 30
      1577105.00      6910638.00      1577080.96      6910460.65
      1577518.21      6910324.37      1578087.92      6909654.14
      1578285.59      6909658.67      1578347.22      6909437.90
      1578343.90      6909327.68      1578049.39      6908993.59
      1577698.79      6908880.19      1577562.29      6908687.91
      1577697.40      6908541.34      1577610.07      6908385.71
      1577847.93      6908138.00      1577614.13      6907894.74
      1577657.07      6907693.86      1577810.62      6907492.81
      1577915.04      6907526.88      1578151.87      6907286.37
      1578105.38      6906653.16      1578247.35      6906434.30
      1578012.97      6906385.06      1577953.59      6906241.06
      1577818.11      6906252.03      1577905.05      6906003.34
      1577768.33      6905851.65      1577695.00      6905876.76
      1577461.67      6905647.30      1577217.95      6905601.63
      1577212.70      6905384.59      1577305.00      6905288.00

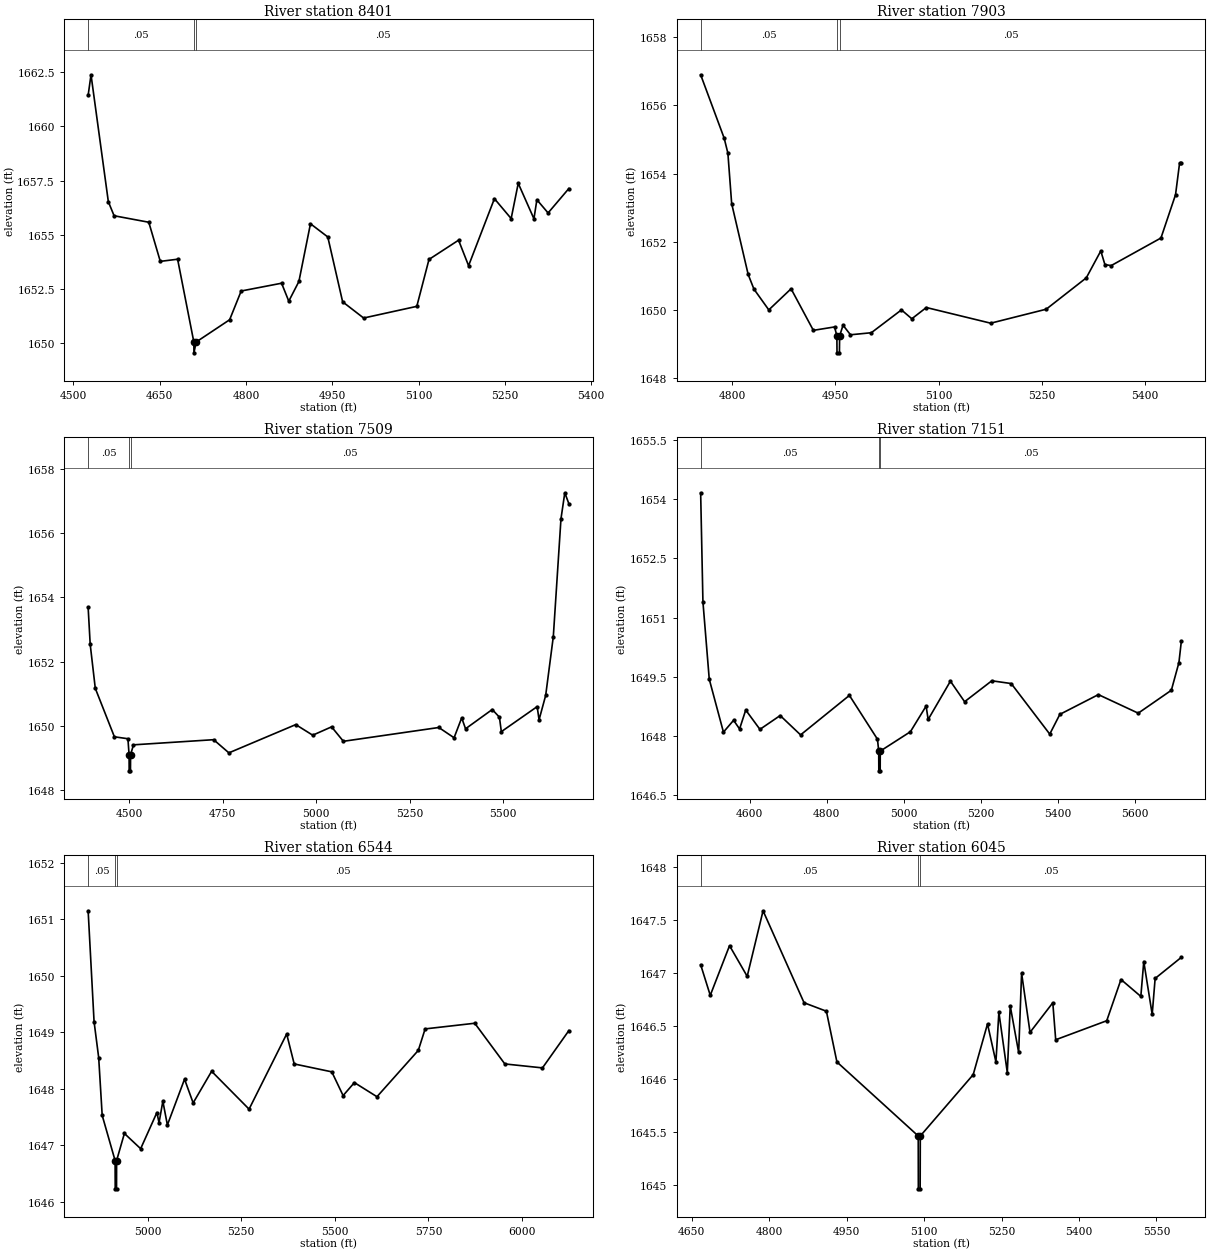
Type RM Length L Ch R = 1,8401,498,498,498
BEGIN DESCRIPTION:
Deadman 18 7.0
END DESCRIPTION:
XS GIS Cut Line= 3
      1577529.96      6910613.00      1577088.70      6910574.60
      1576710.20      6910678.78
#Sta/Elev= 30
  4525.5 1661.44  4530.5 1662.39  4560.6 1656.52  4570.6 1655.87  4630.9 1655.57
  4650.9 1653.76  4681.0 1653.86  4709.2 1650.03  4709.4 1649.53  4713.2 1650.03
  4771.4 1651.06  4791.5 1652.39  4861.7 1652.75  4874.2 1651.92  4891.8 1652.83
  4911.9 1655.50  4942.0 1654.89  4967.8 1651.89  5004.3 1651.14  5096.7 1651.68
  5117.9 1653.85  5169.3 1654.74  5186.7 1653.56  5231.6 1656.66  5260.7 1655.74
  5273.0 1657.37  5300.3 1655.73  5305.4 1656.61  5324.9 1656.00  5361.0 1657.13
#Mann=3,-1,0
  4525.5    0.05       0  4709.2    0.05       0  4713.2    0.05       0
Bank Sta=4709.2,4713.2
Exp/Cntr=0.3,0.1

Type RM Length L Ch R = 1,7903,394,394,394
BEGIN DESCRIPTION:
Mapping XS c17fdcd0
END DESCRIPTION:
XS GIS Cut Line= 3
      1577494.96      6910619.75      1577387.31      6910355.85
      1577040.12      6910130.18
#Sta/Elev= 30
  4754.1 1656.90  4788.3 1655.04  4793.7 1654.60  4799.2 1653.12  4823.2 1651.04
  4831.6 1650.61  4853.2 1650.00  4885.6 1650.62  4918.0 1649.40  4948.8 1649.50
  4952.2 1649.24  4952.4 1648.74  4955.9 1648.74  4956.2 1649.24  4961.2 1649.55
  4972.0 1649.27  5002.3 1649.33  5046.1 1650.00  5061.2 1649.74  5082.3 1650.07
  5175.9 1649.61  5256.6 1650.02  5314.9 1650.94  5336.0 1651.73  5342.0 1651.33
  5351.1 1651.30  5423.5 1652.11  5444.7 1653.38  5450.6 1654.31  5453.2 1654.31
#Mann=3,-1,0
  4754.1    0.05       0  4952.2    0.05       0  4956.2    0.05       0
Bank Sta=4952.2,4956.2
Exp/Cntr=0.3,0.1

Type RM Length L Ch R = 1,7509,358,358,358
BEGIN DESCRIPTION:
Mapping XS 4d58151e
END DESCRIPTION:
XS GIS Cut Line= 2
      1578293.75      6910264.43      1577034.28      6910006.52
#Sta/Elev= 30
  4389.8 1653.69  4395.3 1652.54  4408.9 1651.17  4460.0 1649.66  4496.2 1649.60
  4499.3 1649.10  4499.5 1648.60  4503.0 1648.60  4503.3 1649.10  4511.0 1649.41
  4725.4 1649.57  4766.2 1649.16  4945.0 1650.04  4990.4 1649.71  5040.8 1649.97
  5072.4 1649.52  5327.6 1649.95  5368.4 1649.63  5388.8 1650.25  5399.1 1649.91
  5470.5 1650.51  5489.7 1650.27  5494.8 1649.82  5590.6 1650.60  5595.7 1650.19
  5613.4 1650.95  5633.8 1652.78  5654.3 1656.45  5664.5 1657.26  5675.4 1656.92
#Mann=3,-1,0
  4389.8    0.05       0  4499.3    0.05       0  4503.3    0.05       0
Bank Sta=4499.3,4503.3
Exp/Cntr=0.3,0.1

Type RM Length L Ch R = 1,7151,607,607,607
BEGIN DESCRIPTION:
Mapping XS f6d3b8c3
END DESCRIPTION:
XS GIS Cut Line= 2
      1578350.62      6910060.27      1577168.95      6909663.49
#Sta/Elev= 30
  4473.3 1654.16  4479.2 1651.40  4495.6 1649.44  4532.4 1648.10  4558.7 1648.40
  4574.2 1648.18  4590.2 1648.66  4627.0 1648.17  4679.5 1648.52  4732.4 1648.03
  4859.0 1649.03  4931.8 1647.92  4935.0 1647.62  4935.3 1647.12  4938.8 1647.12
  4939.0 1647.62  5017.2 1648.11  5057.9 1648.76  5063.2 1648.42  5120.9 1649.39
  5157.7 1648.87  5228.2 1649.40  5278.6 1649.33  5378.5 1648.05  5404.7 1648.55
  5504.6 1649.05  5607.9 1648.58  5693.8 1649.16  5713.4 1649.86  5719.8 1650.41
#Mann=3,-1,0
  4473.3    0.05       0  4935.0    0.05       0  4939.0    0.05       0
Bank Sta=4935,4939
Exp/Cntr=0.3,0.1

Type RM Length L Ch R = 1,6544,499,499,499
BEGIN DESCRIPTION:
Mapping XS 4c101bd2
END DESCRIPTION:
XS GIS Cut Line= 3
      1578439.59      6909713.04      1578133.62      6909541.62
      1577204.79      6909628.42
#Sta/Elev= 30
  4841.3 1651.15  4857.1 1649.19  4869.5 1648.55  4878.8 1647.53  4913.3 1646.73
  4913.6 1646.23  4917.1 1646.23  4917.3 1646.73  4938.1 1647.21  4981.5 1646.94
  5024.9 1647.58  5030.6 1647.40  5040.8 1647.78  5052.9 1647.36  5098.7 1648.17
  5121.7 1647.75  5171.0 1648.31  5271.0 1647.64  5371.4 1648.97  5391.5 1648.44
  5491.9 1648.30  5522.1 1647.88  5552.2 1648.11  5612.5 1647.86  5722.9 1648.68
  5741.1 1649.06  5873.6 1649.16  5953.9 1648.44  6054.4 1648.37  6124.9 1649.03
#Mann=3,-1,0
  4841.3    0.05       0  4913.3    0.05       0  4917.3    0.05       0
Bank Sta=4913.3,4917.3
Exp/Cntr=0.3,0.1

Type RM Length L Ch R = 1,6045,247,247,247
BEGIN DESCRIPTION:
Mapping XS 2604aabd
END DESCRIPTION:
XS GIS Cut Line= 3
      1578543.16      6909181.17      1578216.42      6909249.96
      1577688.86      6909528.75
#Sta/Elev= 30
  4667.6 1647.08  4686.2 1646.79  4723.5 1647.26  4757.7 1646.97  4788.4 1647.59
  4867.8 1646.72  4911.0 1646.64  4931.4 1646.16  5088.8 1645.46  5089.0 1644.96
  5092.5 1644.96  5092.8 1645.46  5195.2 1646.04  5222.9 1646.52  5239.2 1646.16
  5244.9 1646.63  5261.2 1646.06  5266.9 1646.69  5283.2 1646.25  5288.9 1647.00
  5305.2 1646.44  5349.3 1646.72  5354.9 1646.37  5453.7 1646.55  5481.3 1646.94
  5519.7 1646.78  5525.4 1647.11  5541.7 1646.61  5547.4 1646.95  5598.2 1647.15
#Mann=3,-1,0
  4667.6    0.05       0  5088.8    0.05       0  5092.8    0.05       0
Bank Sta=5088.8,5092.8
Exp/Cntr=0.3,0.1

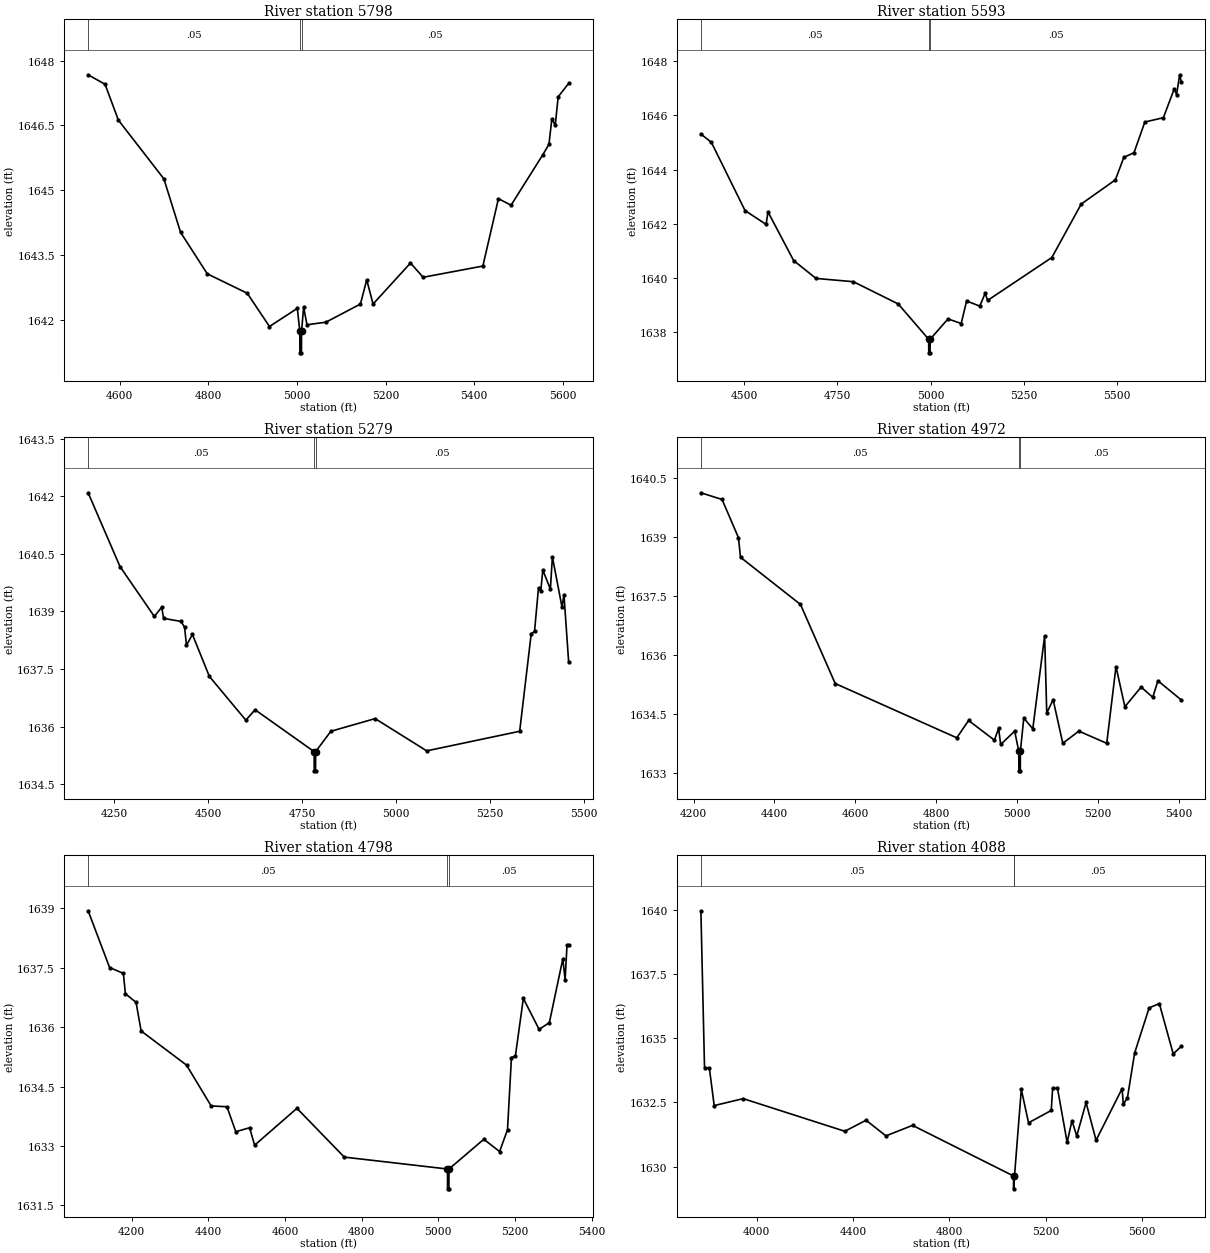
Type RM Length L Ch R = 1,5798,205,205,205
BEGIN DESCRIPTION:
Mapping XS 7f89aab0
END DESCRIPTION:
XS GIS Cut Line= 3
      1578543.09      6909022.13      1578078.86      6909052.22
      1577614.61      6909460.58
#Sta/Elev= 30
  4529.2 1647.67  4567.4 1647.45  4597.4 1646.62  4700.0 1645.26  4737.7 1644.02
  4797.9 1643.06  4888.0 1642.61  4938.1 1641.84  5000.9 1642.26  5006.5 1641.73
  5006.7 1641.23  5010.2 1641.23  5010.5 1641.73  5015.1 1642.29  5022.7 1641.88
  5065.4 1641.94  5143.2 1642.36  5157.4 1642.92  5171.7 1642.36  5256.1 1643.31
  5284.6 1642.98  5419.3 1643.24  5454.4 1644.80  5482.9 1644.65  5554.0 1645.81
  5568.3 1646.06  5574.9 1646.65  5582.5 1646.50  5589.1 1647.16  5612.7 1647.47
#Mann=3,-1,0
  4529.2    0.05       0  5006.5    0.05       0  5010.5    0.05       0
Bank Sta=5006.5,5010.5
Exp/Cntr=0.3,0.1

Type RM Length L Ch R = 1,5593,314,314,314
BEGIN DESCRIPTION:
Mapping XS 63c1dffb
END DESCRIPTION:
XS GIS Cut Line= 3
      1578533.11      6908883.63      1577946.34      6908914.88
      1577519.65      6909469.92
#Sta/Elev= 30
  4384.2 1645.31  4412.4 1645.00  4502.5 1642.49  4559.0 1641.98  4564.0 1642.44
  4632.7 1640.65  4692.7 1639.99  4792.9 1639.87  4913.1 1639.05  4994.6 1637.75
  4994.9 1637.25  4998.4 1637.25  4998.6 1637.75  5046.5 1638.50  5081.8 1638.33
  5096.3 1639.16  5131.6 1638.97  5146.2 1639.45  5152.5 1639.18  5324.7 1640.76
  5403.5 1642.73  5495.0 1643.62  5517.7 1644.45  5544.9 1644.62  5573.9 1645.75
  5623.7 1645.91  5652.7 1646.97  5659.0 1646.76  5667.2 1647.49  5671.9 1647.22
#Mann=3,-1,0
  4384.2    0.05       0  4994.6    0.05       0  4998.6    0.05       0
Bank Sta=4994.6,4998.6
Exp/Cntr=0.3,0.1

Type RM Length L Ch R = 1,5279,307,307,307
BEGIN DESCRIPTION:
Mapping XS 5b11c34a
END DESCRIPTION:
XS GIS Cut Line= 3
      1578448.59      6908845.89      1577881.12      6908751.31
      1577219.54      6908987.59
#Sta/Elev= 30
  4181.4 1642.09  4266.1 1640.17  4357.4 1638.87  4377.0 1639.11  4382.1 1638.82
  4428.3 1638.74  4437.9 1638.59  4442.9 1638.12  4458.8 1638.40  4503.7 1637.31
  4600.7 1636.17  4625.4 1636.44  4782.4 1635.35  4782.7 1634.85  4786.2 1634.85
  4786.4 1635.35  4826.9 1635.88  4944.6 1636.21  5081.8 1635.37  5329.0 1635.88
  5359.7 1638.42  5368.5 1638.48  5379.1 1639.62  5385.2 1639.54  5390.5 1640.08
  5410.7 1639.58  5416.0 1640.42  5441.5 1639.12  5446.8 1639.43  5459.2 1637.69
#Mann=3,-1,0
  4181.4    0.05       0  4782.4    0.05       0  4786.4    0.05       0
Bank Sta=4782.4,4786.4
Exp/Cntr=0.3,0.1

Type RM Length L Ch R = 1,4972,174,174,174
BEGIN DESCRIPTION:
Mapping XS a7456972
END DESCRIPTION:
XS GIS Cut Line= 2
      1578405.54      6908798.59      1577258.92      6908485.10
#Sta/Elev= 30
  4217.9 1640.12  4270.3 1639.95  4310.8 1638.98  4315.9 1638.48  4464.3 1637.28
  4550.2 1635.27  4850.9 1633.89  4880.2 1634.33  4944.1 1633.83  4954.4 1634.13
  4959.6 1633.72  4994.1 1634.06  5004.3 1633.55  5004.6 1633.05  5008.1 1633.05
  5008.3 1633.55  5016.7 1634.39  5039.0 1634.12  5068.3 1636.48  5073.5 1634.52
  5089.3 1634.86  5113.2 1633.75  5152.9 1634.06  5221.9 1633.75  5244.8 1635.70
  5266.8 1634.68  5307.0 1635.18  5335.8 1634.92  5348.5 1635.34  5406.6 1634.85
#Mann=3,-1,0
  4217.9    0.05       0  5004.3    0.05       0  5008.3    0.05       0
Bank Sta=5004.3,5008.3
Exp/Cntr=0.3,0.1

Type RM Length L Ch R = 1,4798,710,710,710
BEGIN DESCRIPTION:
Mapping XS 3137fd01
END DESCRIPTION:
XS GIS Cut Line= 2
      1578516.31      6908686.14      1577300.32      6908380.96
#Sta/Elev= 30
  4086.5 1638.93  4142.5 1637.50  4178.5 1637.35  4183.7 1636.84  4211.6 1636.62
  4224.8 1635.90  4343.2 1635.04  4407.5 1634.01  4448.7 1633.99  4471.8 1633.36
  4507.8 1633.46  4520.9 1633.02  4631.3 1633.95  4754.8 1632.72  5024.1 1632.42
  5024.3 1631.92  5027.8 1631.92  5028.1 1632.42  5118.9 1633.17  5160.1 1632.86
  5180.7 1633.41  5191.0 1635.23  5201.3 1635.27  5222.0 1636.72  5263.2 1635.94
  5289.9 1636.11  5325.1 1637.72  5331.0 1637.19  5336.0 1638.07  5340.2 1638.07
#Mann=3,-1,0
  4086.5    0.05       0  5024.1    0.05       0  5028.1    0.05       0
Bank Sta=5024.1,5028.1
Exp/Cntr=0.3,0.1

Type RM Length L Ch R = 1,4088,728,728,728
BEGIN DESCRIPTION:
Deadman 18 3.0
END DESCRIPTION:
XS GIS Cut Line= 3
      1578880.04      6908063.00      1577655.00      6907938.00
      1576891.22      6907886.67
#Sta/Elev= 30
  3767.8 1639.96  3782.9 1633.86  3803.0 1633.84  3823.1 1632.38  3943.7 1632.65
  4365.9 1631.38  4454.4 1631.81  4536.8 1631.20  4647.4 1631.61  5067.1 1629.64
  5067.3 1629.14  5071.1 1629.64  5099.4 1633.01  5129.5 1631.71  5223.8 1632.19
  5229.7 1633.06  5249.8 1633.05  5289.9 1630.95  5309.9 1631.79  5329.9 1631.20
  5368.5 1632.50  5410.1 1631.03  5518.3 1633.04  5523.3 1632.43  5540.4 1632.68
  5570.5 1634.43  5630.6 1636.18  5673.0 1636.35  5730.8 1634.39  5764.7 1634.69
#Mann=3,-1,0
  3767.8    0.05       0  5067.1    0.05       0  5071.1    0.05       0
Bank Sta=5067.1,5071.1
Exp/Cntr=0.3,0.1

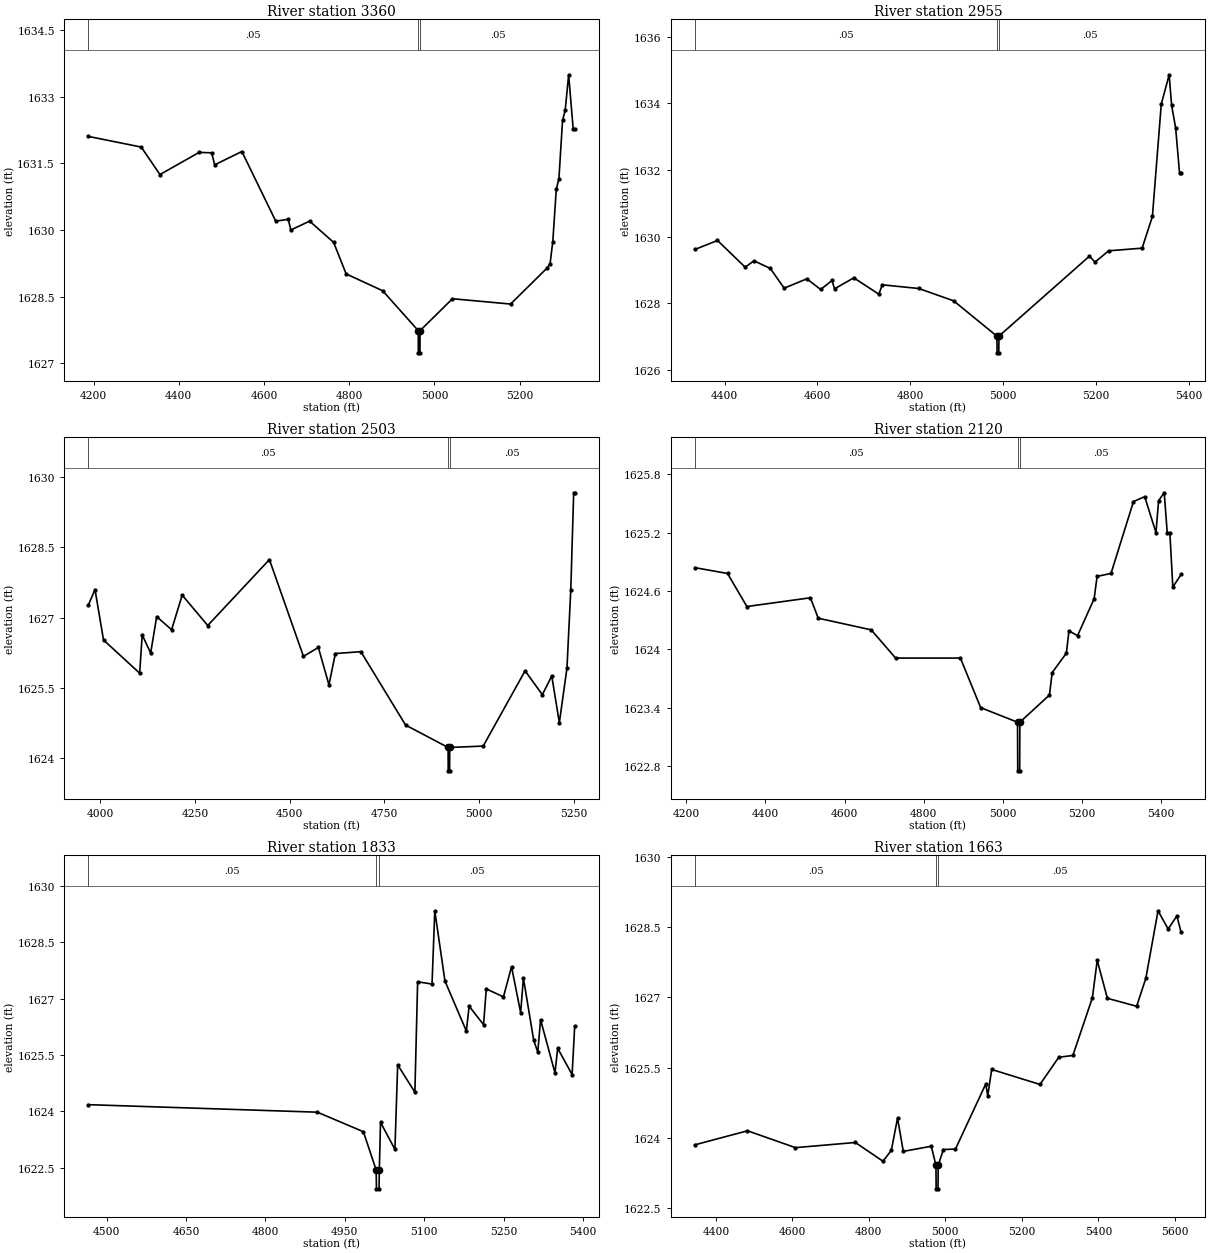
Type RM Length L Ch R = 1,3360,405,405,405
BEGIN DESCRIPTION:
Mapping XS c470933c
END DESCRIPTION:
XS GIS Cut Line= 2
      1578624.06      6907953.25      1577703.58      6907278.67
#Sta/Elev= 30
  4188.0 1632.11  4311.9 1631.87  4355.9 1631.25  4447.8 1631.75  4477.1 1631.74
  4484.4 1631.47  4548.1 1631.77  4627.6 1630.20  4656.9 1630.24  4663.1 1630.00
  4707.1 1630.20  4763.5 1629.72  4792.8 1629.01  4878.5 1628.63  4962.1 1627.73
  4962.3 1627.23  4966.0 1627.23  4966.3 1627.73  5042.3 1628.45  5178.7 1628.33
  5265.2 1629.15  5271.4 1629.24  5277.8 1629.74  5286.0 1630.92  5292.2 1631.16
  5300.7 1632.47  5306.9 1632.70  5315.0 1633.50  5325.6 1632.28  5329.2 1632.28
#Mann=3,-1,0
  4188.0    0.05       0  4962.1    0.03       0  4966.3    0.05       0
Bank Sta=4962.1,4966.3
Exp/Cntr=0.3,0.1

Type RM Length L Ch R = 1,2955,452,452,452
BEGIN DESCRIPTION:
Mapping XS 7c63289f
END DESCRIPTION:
XS GIS Cut Line= 3
      1578723.69      6907401.54      1578115.84      6907162.71
      1577733.59      6907067.15
#Sta/Elev= 30
  4335.9 1629.62  4384.7 1629.89  4444.3 1629.09  4463.3 1629.28  4498.5 1629.05
  4528.3 1628.46  4577.1 1628.74  4606.9 1628.42  4631.3 1628.69  4636.7 1628.44
  4678.3 1628.77  4732.0 1628.28  4739.7 1628.56  4818.0 1628.45  4893.2 1628.08
  4986.4 1627.02  4986.7 1626.52  4990.4 1626.52  4990.7 1627.02  5185.7 1629.42
  5197.6 1629.24  5226.9 1629.58  5299.1 1629.66  5321.2 1630.61  5340.3 1633.98
  5357.3 1634.86  5362.5 1633.95  5371.2 1633.27  5379.7 1631.91  5383.0 1631.91
#Mann=3,-1,0
  4335.9    0.05       0  4986.4    0.05       0  4990.7    0.05       0
Bank Sta=4986.4,4990.7
Exp/Cntr=0.3,0.1

Type RM Length L Ch R = 1,2503,383,383,383
BEGIN DESCRIPTION:
Mapping XS 2d548c95
END DESCRIPTION:
XS GIS Cut Line= 3
      1579042.28      6907152.30      1578229.76      6906751.25
      1577854.74      6906714.79
#Sta/Elev= 30
  3969.0 1627.27  3986.4 1627.60  4008.8 1626.52  4104.2 1625.81  4110.9 1626.63
  4133.2 1626.24  4149.1 1627.02  4188.4 1626.74  4216.4 1627.48  4283.8 1626.83
  4446.5 1628.24  4536.3 1626.17  4575.6 1626.36  4603.6 1625.56  4620.5 1626.23
  4687.8 1626.27  4805.7 1624.70  4917.9 1624.22  4918.2 1623.72  4921.9 1623.72
  4922.2 1624.22  5010.5 1624.25  5121.0 1625.86  5166.6 1625.35  5191.4 1625.75
  5211.4 1624.75  5231.5 1625.92  5241.6 1627.60  5249.2 1629.67  5251.9 1629.67
#Mann=3,-1,0
  3969.0    0.05       0  4917.9    0.05       0  4922.2    0.05       0
Bank Sta=4917.9,4922.2
Exp/Cntr=0.3,0.1

Type RM Length L Ch R = 1,2120,287,287,287
BEGIN DESCRIPTION:
Mapping XS 7a9a32cd
END DESCRIPTION:
XS GIS Cut Line= 3
      1578990.23      6906245.18      1578207.82      6906417.13
      1577891.05      6906703.94
#Sta/Elev= 30
  4221.8 1624.84  4304.4 1624.78  4353.3 1624.44  4513.8 1624.53  4533.5 1624.32
  4667.4 1624.20  4729.0 1623.91  4892.7 1623.91  4943.9 1623.40  5037.0 1623.25
  5037.5 1622.75  5042.4 1622.75  5042.9 1623.25  5117.7 1623.53  5124.4 1623.76
  5160.3 1623.96  5167.0 1624.19  5188.6 1624.14  5230.5 1624.52  5238.0 1624.75
  5273.1 1624.78  5329.9 1625.52  5358.3 1625.57  5386.7 1625.20  5393.4 1625.53
  5407.6 1625.61  5415.1 1625.20  5421.8 1625.20  5429.3 1624.64  5450.2 1624.77
#Mann=3,-1,0
  4221.8    0.05       0  5037.0   0.035       0  5042.9    0.05       0
Bank Sta=5037,5042.9
Exp/Cntr=0.3,0.1

Type RM Length L Ch R = 1,1833,170,170,170
BEGIN DESCRIPTION:
Mapping XS 851c0c9f
END DESCRIPTION:
XS GIS Cut Line= 2
      1578164.82      6905815.35      1577889.85      6906691.83
#Sta/Elev= 30
  4465.8 1624.18  4898.3 1623.98  4985.2 1623.46  5009.4 1622.44  5009.9 1621.94
  5014.8 1621.94  5015.3 1622.44  5017.6 1623.71  5044.8 1622.99  5050.0 1625.24
  5082.5 1624.51  5087.7 1627.45  5114.9 1627.39  5120.1 1629.34  5139.3 1627.47
  5179.7 1626.14  5185.0 1626.80  5212.2 1626.31  5217.4 1627.26  5249.8 1627.05
  5265.1 1627.85  5282.3 1626.63  5287.5 1627.55  5307.0 1625.89  5314.7 1625.58
  5319.9 1626.44  5347.1 1625.03  5352.3 1625.68  5379.5 1624.98  5384.4 1626.27
#Mann=3,-1,0
  4465.8    0.05       0  5009.4   0.035       0  5015.3    0.05       0
Bank Sta=5009.4,5015.3
Exp/Cntr=0.3,0.1

Type RM Length L Ch R = 1,1663,1164,1164,1164
BEGIN DESCRIPTION:
Mapping XS a732d967
END DESCRIPTION:
XS GIS Cut Line= 3
      1578083.16      6905626.17      1577906.91      6906210.80
      1577700.57      6906838.43
#Sta/Elev= 30
  4345.0 1623.85  4482.7 1624.15  4608.0 1623.79  4764.7 1623.90  4836.8 1623.50
  4858.7 1623.73  4875.0 1624.42  4890.0 1623.71  4963.2 1623.82  4975.4 1623.41
  4975.9 1622.91  4980.8 1622.91  4981.3 1623.41  4994.8 1623.75  5026.4 1623.76
  5105.6 1625.15  5110.8 1624.90  5121.1 1625.46  5247.4 1625.14  5296.4 1625.72
  5333.4 1625.76  5384.3 1626.99  5397.0 1627.79  5423.6 1626.98  5500.1 1626.81
  5524.2 1627.41  5556.0 1628.85  5582.5 1628.46  5605.3 1628.74  5616.3 1628.39
#Mann=3,-1,0
  4345.0    0.05       0  4975.4    0.05       0  4981.3    0.05       0
Bank Sta=4975.4,4981.3
Exp/Cntr=0.3,0.1

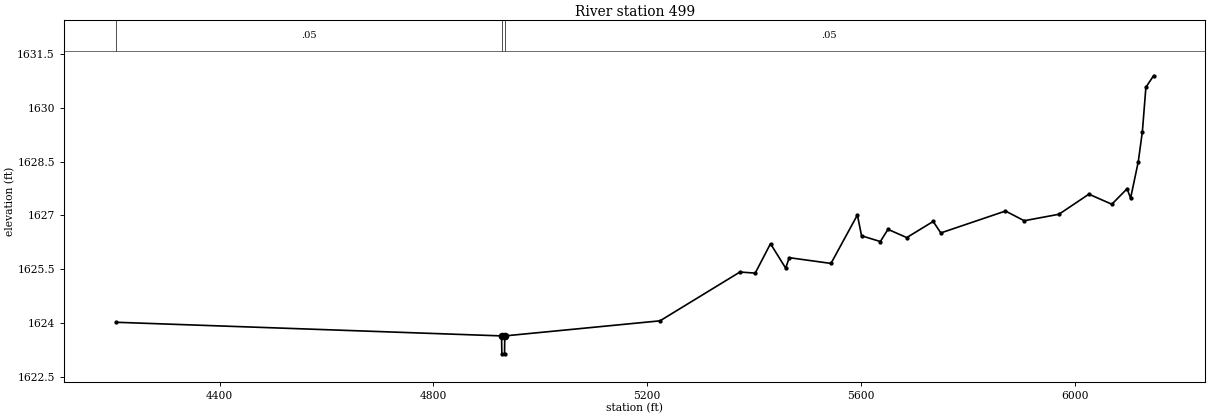
Type RM Length L Ch R = 1,499,0,0,0
BEGIN DESCRIPTION:
Deadman 18 2.0
END DESCRIPTION:
XS GIS Cut Line= 3
      1578108.94      6905608.98      1577330.89      6905626.18
      1576579.97      6906513.03
#Sta/Elev= 30
  4206.4 1624.02  4927.5 1623.64  4928.0 1623.14  4933.0 1623.14  4933.5 1623.64
  5223.8 1624.06  5373.2 1625.42  5401.8 1625.39  5430.4 1626.21  5458.7 1625.53
  5465.5 1625.82  5543.5 1625.66  5592.9 1627.01  5600.7 1626.43  5635.8 1626.27
  5650.1 1626.61  5685.2 1626.38  5734.6 1626.83  5748.9 1626.51  5869.8 1627.12
  5904.9 1626.85  5969.8 1627.03  6025.8 1627.59  6068.7 1627.31  6097.2 1627.74
  6103.8 1627.48  6118.1 1628.49  6125.8 1629.33  6132.4 1630.57  6146.7 1630.89
#Mann=3,-1,0
  4206.4    0.05       0  4927.5   0.035       0  4933.5    0.05       0
Bank Sta=4927.5,4933.5
Exp/Cntr=0.3,0.1

Chan Stop Cuts=-1