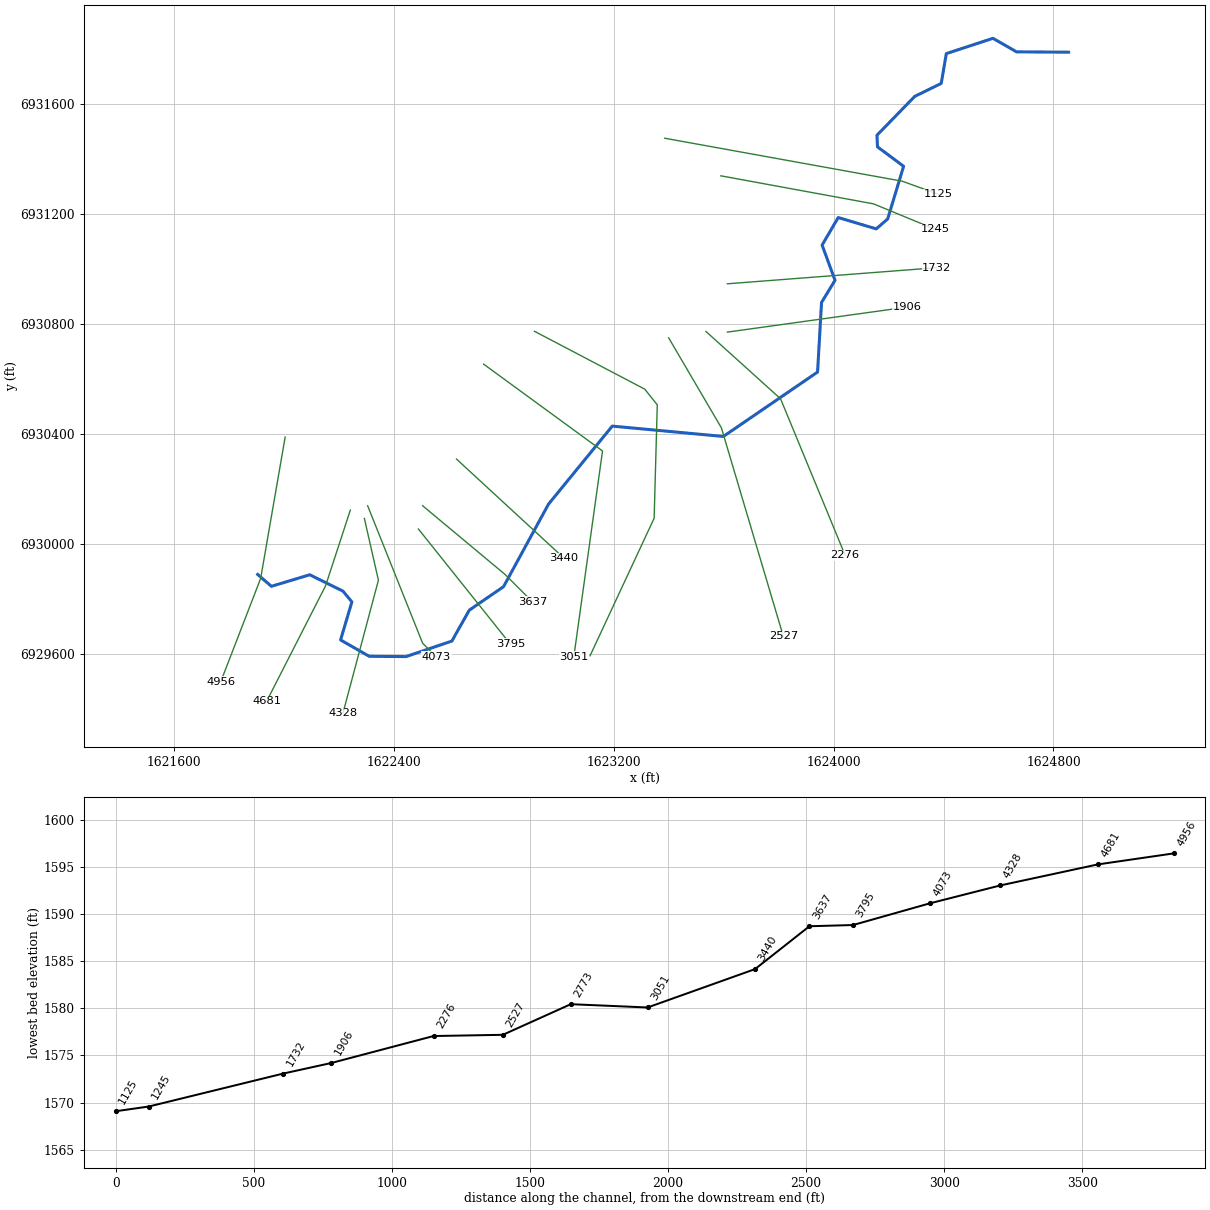
--- Deadman 19.prj (project) ---

Proj Title=Deadman 19 Base Level Engineering
Current Plan=p01
Default Exp/Contr=0.3,0.1
English Units
Geom File=g01
Flow File=f01
Plan File=p01
BEGIN DESCRIPTION:
Deadman 19
END DESCRIPTION:

--- Deadman 19.p01 (plan) ---

Plan Title=Multiple Run
Short Identifier=Multiple
Geom File=g01
Flow File=f01
Subcritical Flow
K Sum by GR= 0
Std Step Tol= 0.01
Critical Tol= 0.01
Num of Std Step Trials= 20
Max Error Tol= 0.3
Flow Tol Ratio= 0.001
Split Flow NTrial= 30
Split Flow Tol= 0.02
Split Flow Ratio= 0.02
Log Output Level= 0
Friction Slope Method= 1
Unsteady Friction Slope Method= 2
Unsteady Bridges Friction Slope Method= 1
Parabolic Critical Depth
Global Vel Dist=  1 , 1 , 1
Global Log Level= 0
CheckData=True
Encroach Param= -1, 0, 0, 0
BEGIN DESCRIPTION:
Multiple Run
END DESCRIPTION:

--- Deadman 19.f01 (steady flow) ---

Flow Title=Multiple
Number of Profiles=7
Profile Names=10-year,25-year,50-year,1pct_min,100-year,1pct_plu,500-year
River Rch & RM= Deadman 19,Reach-1,4956
     177     237     285     171     341     679     493
River Rch & RM= Deadman 19,Reach-1,4681
     208     282     341     206     411     821     605
River Rch & RM= Deadman 19,Reach-1,1732
     237     324     394     239     478     953     709
Boundary for River Rch & Prof#=Deadman 19,Reach-1,1
Up Type=0
Dn Type=3
Dn Slope=0.005
Boundary for River Rch & Prof#=Deadman 19,Reach-1,2
Up Type=0
Dn Type=3
Dn Slope=0.005
Boundary for River Rch & Prof#=Deadman 19,Reach-1,3
Up Type=0
Dn Type=3
Dn Slope=0.005
Boundary for River Rch & Prof#=Deadman 19,Reach-1,4
Up Type=0
Dn Type=3
Dn Slope=0.005
Boundary for River Rch & Prof#=Deadman 19,Reach-1,5
Up Type=0
Dn Type=3
Dn Slope=0.005
Boundary for River Rch & Prof#=Deadman 19,Reach-1,6
Up Type=0
Dn Type=3
Dn Slope=0.005
Boundary for River Rch & Prof#=Deadman 19,Reach-1,7
Up Type=0
Dn Type=3
Dn Slope=0.005

--- Deadman 19.g01 (geometry) ---

Geom Title=Existing Conditions

River Reach=Deadman 19,Reach-1
Reach XY= 30
      1621905.00      6929888.00      1621954.86      6929844.91
      1622094.46      6929886.91      1622215.42      6929827.25
      1622247.77      6929788.31      1622206.51      6929649.86
      1622310.91      6929590.22      1622444.49      6929589.20
      1622611.45      6929645.74      1622674.78      6929758.12
      1622799.38      6929843.62      1622963.14      6930144.06
      1623194.90      6930427.70      1623599.14      6930390.06
      1623941.77      6930624.33      1623956.24      6930877.50
      1624005.28      6930958.18      1623958.33      6931086.31
      1624016.85      6931186.49      1624155.31      6931145.23
      1624196.87      6931181.30      1624254.79      6931372.90
      1624159.77      6931443.64      1624157.95      6931485.99
      1624295.34      6931627.21      1624391.73      6931674.38
      1624410.11      6931782.89      1624580.00      6931838.40
      1624665.49      6931789.23      1624855.00      6931788.00

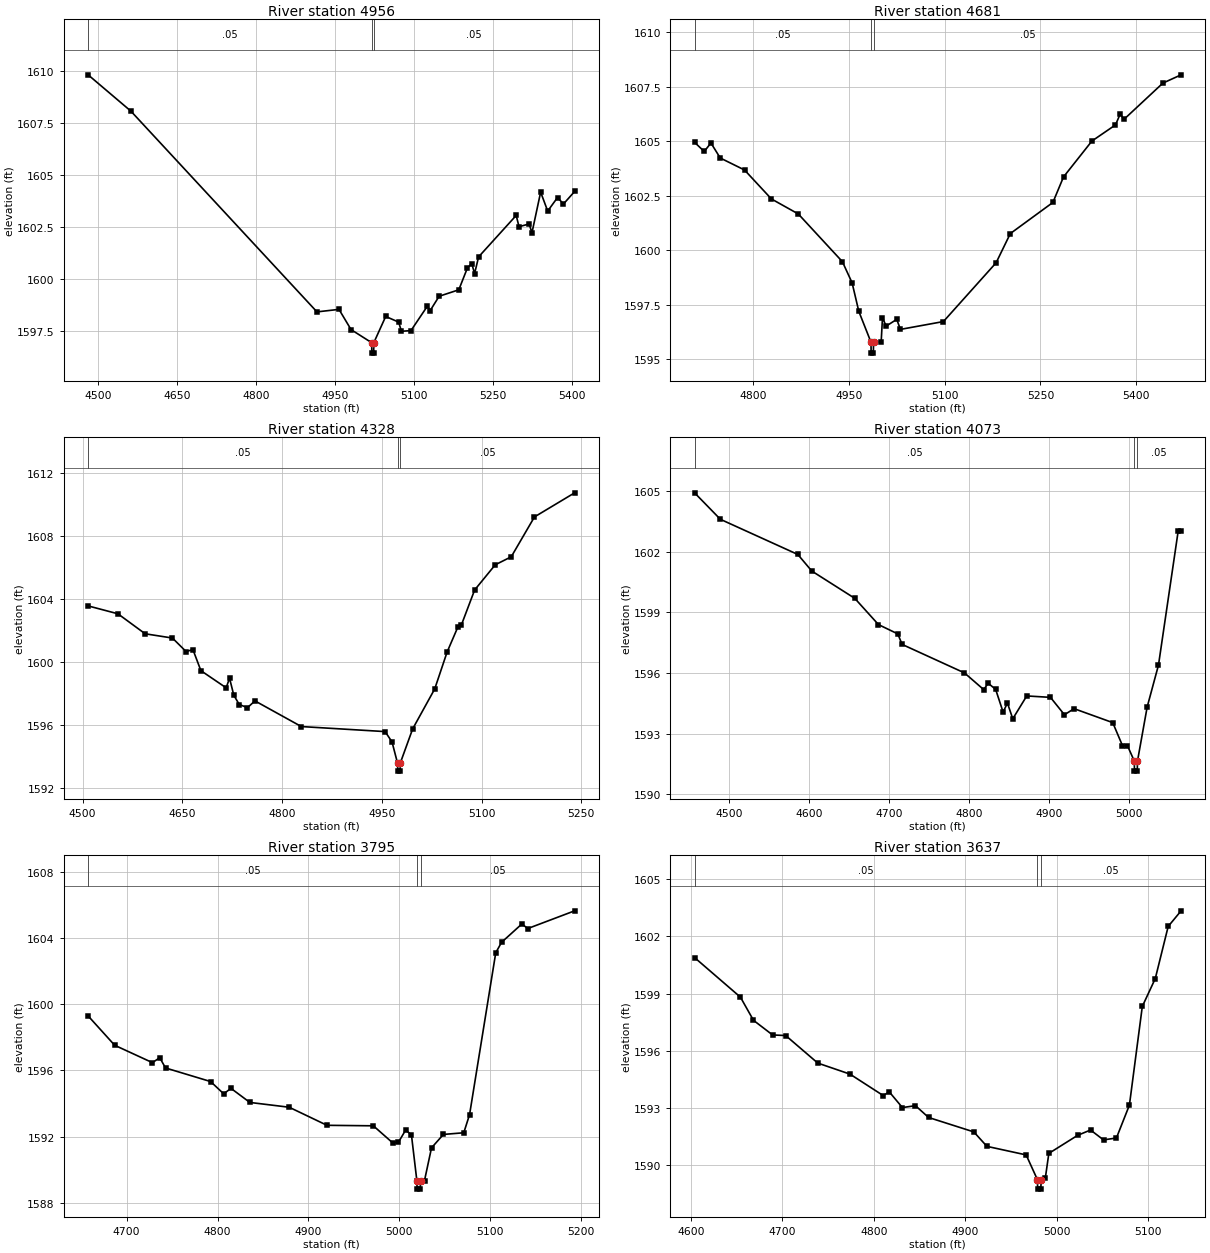
Type RM Length L Ch R = 1,4956,275,275,275
BEGIN DESCRIPTION:
Deadman 19 5.0
END DESCRIPTION:
XS GIS Cut Line= 3
      1622004.99      6930387.96      1621915.76      6929873.41
      1621770.60      6929497.71
#Sta/Elev= 30
  4480.7 1609.80  4561.9 1608.06  4915.8 1598.42  4957.7 1598.54  4980.6 1597.57
  5019.9 1596.94  5020.1 1596.44  5023.6 1596.44  5023.9 1596.94  5046.5 1598.20
  5071.1 1597.93  5076.4 1597.49  5094.5 1597.52  5125.6 1598.69  5131.0 1598.48
  5148.1 1599.17  5185.5 1599.48  5201.7 1600.52  5210.1 1600.74  5215.5 1600.26
  5223.1 1601.06  5294.6 1603.05  5300.0 1602.51  5319.2 1602.64  5324.6 1602.22
  5341.1 1604.17  5354.5 1603.26  5373.2 1603.91  5384.5 1603.60  5405.7 1604.20
#Mann=3,-1,0
  4480.7    0.05       0  5019.9    0.05       0  5023.9    0.05       0
Bank Sta=5019.9,5023.9
Exp/Cntr=0.3,0.1

Type RM Length L Ch R = 1,4681,353,353,353
BEGIN DESCRIPTION:
Mapping XS 353da1e4
END DESCRIPTION:
XS GIS Cut Line= 3
      1622242.12      6930122.36      1622151.95      6929846.74
      1621937.60      6929426.55
#Sta/Elev= 30
  4708.6 1604.95  4723.7 1604.53  4734.2 1604.92  4748.8 1604.23  4786.8 1603.68
  4828.9 1602.35  4871.0 1601.66  4940.0 1599.47  4955.2 1598.50  4965.7 1597.19
  4984.8 1595.77  4985.0 1595.27  4988.5 1595.27  4988.8 1595.77  5000.7 1595.77
  5002.8 1596.90  5008.5 1596.51  5025.1 1596.82  5030.9 1596.36  5098.2 1596.72
  5180.7 1599.42  5202.9 1600.76  5269.6 1602.19  5286.2 1603.36  5330.7 1605.01
  5367.6 1605.75  5375.1 1606.26  5380.7 1606.00  5441.8 1607.67  5470.3 1608.05
#Mann=3,-1,0
  4708.6    0.05       0  4984.8    0.03       0  4988.8    0.05       0
Bank Sta=4984.8,4988.8
Exp/Cntr=0.3,0.1

Type RM Length L Ch R = 1,4328,255,255,255
BEGIN DESCRIPTION:
Mapping XS 4005f294
END DESCRIPTION:
XS GIS Cut Line= 3
      1622293.15      6930091.69      1622344.18      6929867.16
      1622214.98      6929382.65
#Sta/Elev= 30
  4508.3 1603.53  4553.1 1603.03  4594.1 1601.76  4635.1 1601.49  4655.7 1600.63
  4665.9 1600.76  4677.9 1599.42  4715.9 1598.33  4721.0 1598.94  4727.4 1597.86
  4735.6 1597.27  4748.0 1597.07  4759.2 1597.50  4829.0 1595.87  4955.0 1595.55
  4965.4 1594.89  4973.7 1593.54  4974.0 1593.04  4977.5 1593.04  4977.7 1593.54
  4996.4 1595.72  5029.6 1598.26  5048.2 1600.60  5064.5 1602.20  5069.7 1602.32
  5089.6 1604.54  5120.6 1606.14  5144.7 1606.65  5179.6 1609.18  5240.0 1610.71
#Mann=3,-1,0
  4508.3    0.05       0  4973.7    0.05       0  4977.7    0.05       0
Bank Sta=4973.7,4977.7
Exp/Cntr=0.3,0.1

Type RM Length L Ch R = 1,4073,278,278,278
BEGIN DESCRIPTION:
Deadman 19 4.0
END DESCRIPTION:
XS GIS Cut Line= 3
      1622304.99      6930138.03      1622505.00      6929638.00
      1622555.03      6929587.97
#Sta/Elev= 30
  4456.3 1604.91  4488.6 1603.60  4585.6 1601.86  4603.1 1601.04  4656.9 1599.69
  4686.6 1598.39  4710.8 1597.93  4716.2 1597.41  4794.3 1596.00  4818.5 1595.17
  4823.9 1595.49  4833.3 1595.19  4842.7 1594.06  4848.1 1594.51  4854.8 1593.73
  4872.3 1594.86  4902.0 1594.79  4919.5 1593.93  4931.6 1594.23  4980.0 1593.54
  4992.2 1592.40  4998.4 1592.40  5007.0 1591.64  5007.2 1591.14  5010.7 1591.14
  5011.0 1591.64  5023.1 1594.31  5037.3 1596.39  5062.0 1603.03  5065.6 1603.03
#Mann=3,-1,0
  4456.3    0.05       0  5007.0    0.05       0  5011.0    0.05       0
Bank Sta=5007,5011
Exp/Cntr=0.3,0.1

Type RM Length L Ch R = 1,3795,158,158,158
BEGIN DESCRIPTION:
Mapping XS 2c096fbb
END DESCRIPTION:
XS GIS Cut Line= 2
      1622489.78      6930053.25      1622823.95      6929634.94
#Sta/Elev= 30
  4657.6 1599.29  4686.8 1597.52  4728.4 1596.47  4736.4 1596.77  4742.8 1596.15
  4792.4 1595.33  4806.8 1594.59  4814.8 1594.92  4835.6 1594.07  4878.9 1593.78
  4920.5 1592.69  4971.5 1592.66  4992.6 1591.64  4999.0 1591.66  5007.0 1592.40
  5013.4 1592.12  5019.4 1589.34  5019.6 1588.84  5023.1 1588.84  5023.4 1589.34
  5027.8 1589.36  5035.5 1591.33  5048.6 1592.14  5071.0 1592.24  5077.4 1593.34
  5106.2 1603.10  5112.6 1603.73  5135.0 1604.84  5141.4 1604.56  5193.0 1605.63
#Mann=3,-1,0
  4657.6    0.05       0  5019.4    0.05       0  5023.4    0.05       0
Bank Sta=5019.4,5023.4
Exp/Cntr=0.3,0.1

Type RM Length L Ch R = 1,3637,197,197,197
BEGIN DESCRIPTION:
Deadman 19 3.0
END DESCRIPTION:
XS GIS Cut Line= 3
      1622505.00      6930138.00      1622805.00      6929888.00
      1622904.97      6929788.03
#Sta/Elev= 30
  4604.0 1600.89  4654.1 1598.81  4668.4 1597.59  4689.3 1596.82  4703.6 1596.79
  4738.7 1595.34  4773.9 1594.76  4810.3 1593.63  4816.8 1593.83  4831.2 1593.00
  4845.5 1593.10  4859.8 1592.48  4909.3 1591.72  4923.6 1590.96  4966.5 1590.51
  4978.8 1589.21  4979.1 1588.71  4982.6 1588.71  4982.8 1589.21  4987.4 1589.27
  4991.3 1590.59  5022.8 1591.54  5036.9 1591.82  5051.1 1591.30  5065.2 1591.40
  5079.4 1593.13  5093.5 1598.32  5107.7 1599.79  5121.8 1602.53  5135.9 1603.35
#Mann=3,-1,0
  4604.0    0.05       0  4978.8    0.05       0  4982.8    0.05       0
Bank Sta=4978.8,4982.8
Exp/Cntr=0.3,0.1

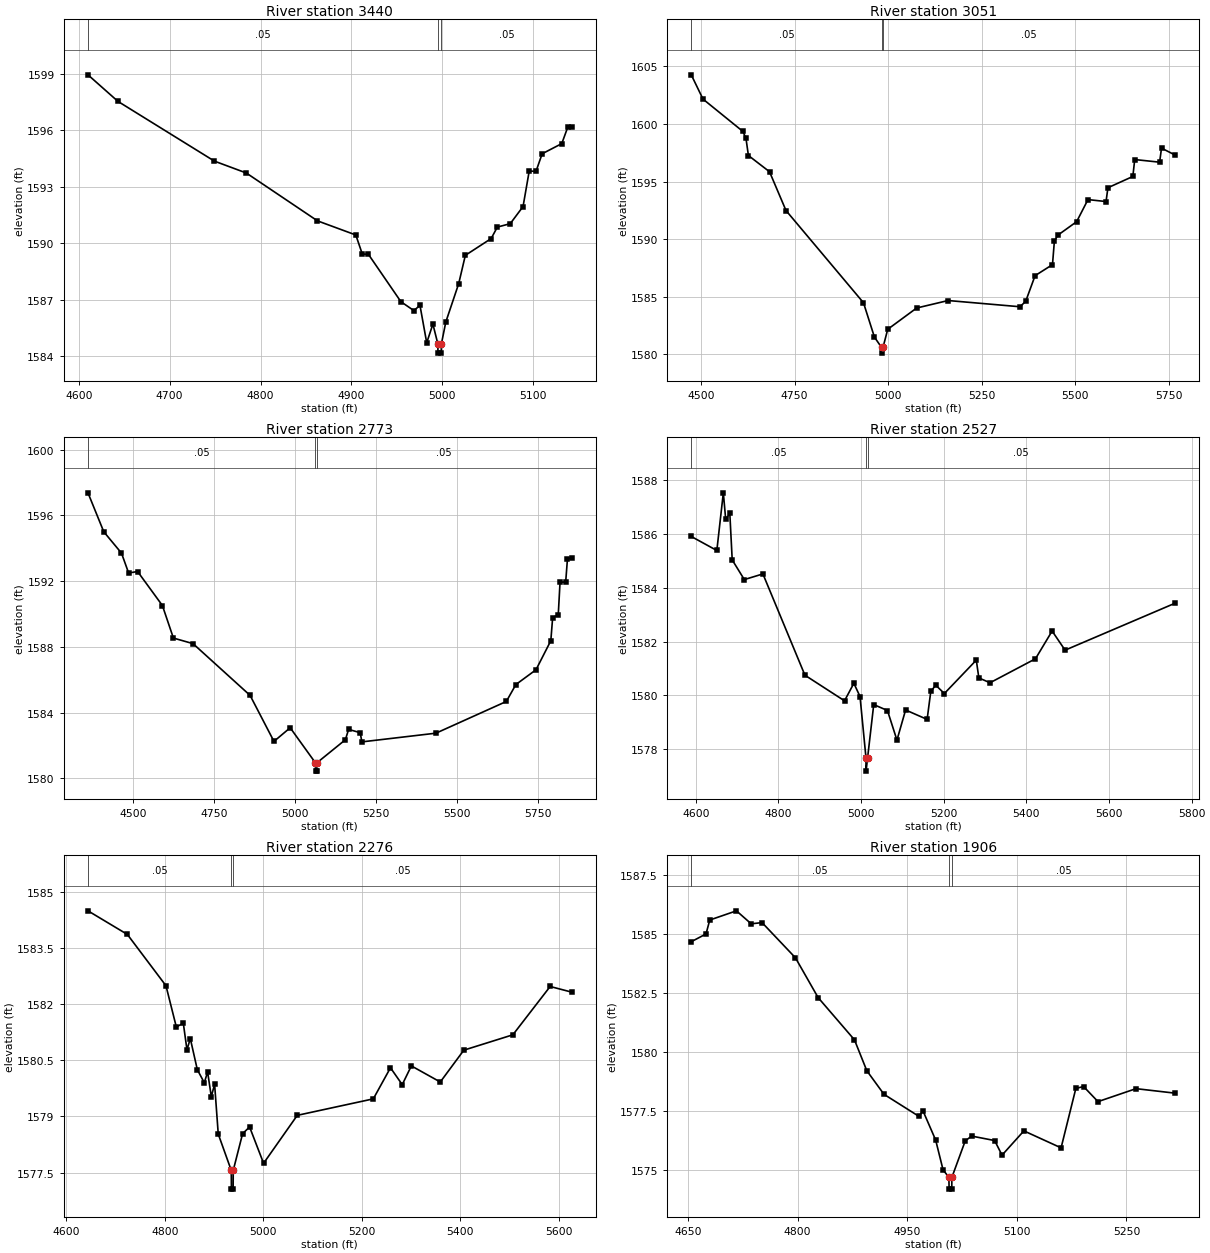
Type RM Length L Ch R = 1,3440,389,389,389
BEGIN DESCRIPTION:
Mapping XS 1ac03470
END DESCRIPTION:
XS GIS Cut Line= 2
      1622628.29      6930307.75      1623019.54      6929947.12
#Sta/Elev= 30
  4610.1 1598.93  4643.1 1597.52  4749.2 1594.35  4784.3 1593.72  4862.6 1591.18
  4904.8 1590.43  4911.9 1589.42  4918.7 1589.40  4954.4 1586.89  4968.6 1586.42
  4975.4 1586.69  4982.8 1584.71  4989.6 1585.70  4995.0 1584.66  4995.2 1584.16
  4998.7 1584.16  4999.0 1584.66  5003.8 1585.81  5018.0 1587.85  5025.3 1589.35
  5053.7 1590.24  5060.5 1590.85  5074.7 1591.03  5088.8 1591.94  5095.6 1593.83
  5103.0 1593.80  5109.8 1594.74  5131.4 1595.28  5137.9 1596.14  5142.2 1596.14
#Mann=3,-1,0
  4610.1    0.05       0  4995.0    0.05       0  4999.0    0.05       0
Bank Sta=4995,4999
Exp/Cntr=0.3,0.1

Type RM Length L Ch R = 1,3051,278,278,278
BEGIN DESCRIPTION:
Deadman 19 2.0
END DESCRIPTION:
XS GIS Cut Line= 3
      1622726.90      6930653.17      1623159.44      6930337.30
      1623055.01      6929588.04
#Sta/Elev= 30
  4473.9 1604.27  4505.3 1602.16  4611.9 1599.35  4620.1 1598.74  4626.6 1597.26
  4683.0 1595.85  4727.0 1592.48  4934.0 1584.47  4963.3 1581.48  4982.2 1580.59
  4982.4 1580.09  4986.2 1580.59  4998.8 1582.16  5076.1 1584.01  5160.2 1584.66
  5352.1 1584.12  5367.4 1584.59  5392.5 1586.82  5439.0 1587.78  5444.0 1589.80
  5453.0 1590.33  5503.5 1591.51  5533.8 1593.43  5582.1 1593.26  5587.1 1594.46
  5653.7 1595.44  5658.7 1596.91  5725.2 1596.68  5730.3 1597.90  5766.0 1597.31
#Mann=3,-1,0
  4473.9    0.05       0  4982.2    0.05       0  4986.2    0.05       0
Bank Sta=4982.2,4986.2
Exp/Cntr=0.3,0.1

Type RM Length L Ch R = 1,2773,246,246,246
BEGIN DESCRIPTION:
Mapping XS d9c90e88
END DESCRIPTION:
XS GIS Cut Line= 5
      1622911.85      6930772.72      1623313.12      6930562.13
      1623358.66      6930505.21      1623347.27      6930092.55
      1623114.23      6929592.35
#Sta/Elev= 30
  4361.7 1597.38  4410.4 1595.01  4465.0 1593.71  4487.0 1592.50  4514.7 1592.59
  4591.1 1590.52  4625.0 1588.54  4685.5 1588.20  4861.4 1585.05  4935.0 1582.25
  4985.0 1583.08  5063.0 1580.94  5063.3 1580.44  5066.8 1580.44  5067.0 1580.94
  5155.1 1582.35  5165.1 1582.98  5200.9 1582.78  5205.9 1582.22  5434.3 1582.75
  5651.2 1584.68  5680.7 1585.71  5742.7 1586.61  5788.4 1588.38  5794.0 1589.78
  5811.3 1589.96  5816.8 1591.94  5834.2 1591.95  5839.7 1593.37  5852.4 1593.41
#Mann=3,-1,0
  4361.7    0.05       0  5063.0    0.03       0  5067.0    0.05       0
Bank Sta=5063,5067
Exp/Cntr=0.3,0.1

Type RM Length L Ch R = 1,2527,251,251,251
BEGIN DESCRIPTION:
Mapping XS 0d3a9e2a
END DESCRIPTION:
XS GIS Cut Line= 3
      1623400.08      6930748.82      1623592.03      6930421.18
      1623817.11      6929663.22
#Sta/Elev= 30
  4589.0 1585.90  4650.9 1585.38  4666.6 1587.52  4672.4 1586.53  4682.3 1586.76
  4688.1 1585.03  4717.4 1584.30  4762.4 1584.51  4864.1 1580.75  4959.9 1579.80
  4982.5 1580.45  4997.4 1579.96  5011.8 1577.69  5012.0 1577.19  5015.8 1577.69
  5030.6 1579.66  5063.8 1579.44  5086.8 1578.34  5107.7 1579.46  5159.8 1579.11
  5168.7 1580.15  5180.7 1580.38  5201.5 1580.07  5278.8 1581.31  5285.0 1580.65
  5312.0 1580.47  5422.0 1581.36  5462.3 1582.39  5493.7 1581.68  5759.4 1583.42
#Mann=3,-1,0
  4589.0    0.05       0  5011.8    0.05       0  5015.8    0.05       0
Bank Sta=5011.8,5015.8
Exp/Cntr=0.3,0.1

Type RM Length L Ch R = 1,2276,370,370,370
BEGIN DESCRIPTION:
Mapping XS fc6c28b8
END DESCRIPTION:
XS GIS Cut Line= 3
      1623535.74      6930772.04      1623807.16      6930527.09
      1624042.16      6929957.79
#Sta/Elev= 30
  4644.3 1584.49  4724.2 1583.86  4802.6 1582.49  4823.6 1581.39  4837.8 1581.49
  4845.2 1580.78  4852.0 1581.08  4866.2 1580.25  4880.4 1579.90  4887.1 1580.19
  4894.6 1579.53  4901.3 1579.86  4908.7 1578.53  4935.1 1577.56  4935.4 1577.06
  4938.9 1577.06  4939.1 1577.56  4958.1 1578.54  4972.3 1578.72  5000.7 1577.75
  5069.1 1579.03  5223.4 1579.47  5258.2 1580.30  5282.1 1579.85  5300.6 1580.35
  5359.3 1579.92  5407.1 1580.77  5506.6 1581.18  5582.3 1582.47  5625.8 1582.32
#Mann=3,-1,0
  4644.3    0.05       0  4935.1    0.05       0  4939.1    0.05       0
Bank Sta=4935.1,4939.1
Exp/Cntr=0.3,0.1

Type RM Length L Ch R = 1,1906,174,174,174
BEGIN DESCRIPTION:
Mapping XS 13c2f888
END DESCRIPTION:
XS GIS Cut Line= 2
      1623613.81      6930769.68      1624269.21      6930860.83
#Sta/Elev= 30
  4654.6 1584.69  4674.8 1585.02  4679.9 1585.61  4716.4 1586.00  4736.6 1585.45
  4751.5 1585.50  4797.1 1584.01  4828.2 1582.32  4877.9 1580.53  4894.8 1579.22
  4918.3 1578.22  4966.4 1577.28  4971.5 1577.53  4989.0 1576.28  4999.1 1575.02
  5007.1 1574.70  5007.4 1574.20  5011.0 1574.20  5011.2 1574.70  5029.4 1576.24
  5038.1 1576.45  5069.7 1576.26  5079.8 1575.64  5109.7 1576.67  5160.6 1575.95
  5180.8 1578.47  5191.4 1578.55  5211.1 1577.91  5263.1 1578.46  5316.3 1578.27
#Mann=3,-1,0
  4654.6    0.05       0  5007.1    0.05       0  5011.2    0.05       0
Bank Sta=5007.1,5011.2
Exp/Cntr=0.3,0.1

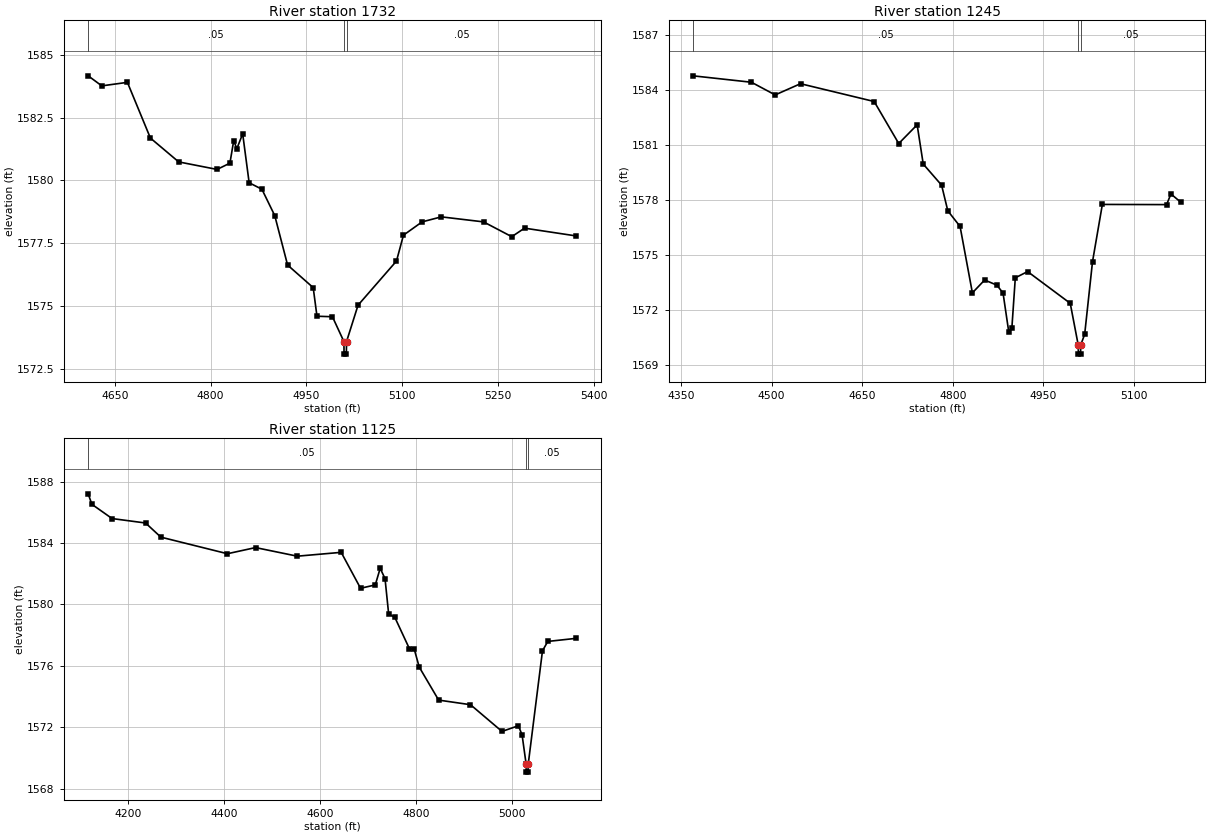
Type RM Length L Ch R = 1,1732,487,487,487
BEGIN DESCRIPTION:
Mapping XS 9e3cfe6d
END DESCRIPTION:
XS GIS Cut Line= 2
      1623613.77      6930945.45      1624375.52      6931004.05
#Sta/Elev= 30
  4608.3 1584.17  4629.6 1583.77  4669.7 1583.91  4705.7 1581.69  4750.0 1580.74
  4810.1 1580.44  4830.2 1580.69  4836.1 1581.58  4841.1 1581.27  4850.2 1581.86
  4860.3 1579.91  4880.3 1579.65  4900.4 1578.60  4920.5 1576.63  4960.6 1575.73
  4966.5 1574.59  4990.7 1574.57  5008.7 1573.58  5008.9 1573.08  5012.5 1573.08
  5012.8 1573.58  5030.8 1575.03  5091.0 1576.79  5101.9 1577.82  5131.1 1578.35
  5161.2 1578.55  5227.3 1578.35  5271.5 1577.76  5291.5 1578.10  5372.3 1577.79
#Mann=3,-1,0
  4608.3    0.05       0  5008.7    0.03       0  5012.8    0.05       0
Bank Sta=5008.7,5012.8
Exp/Cntr=0.3,0.1

Type RM Length L Ch R = 1,1245,120,120,120
BEGIN DESCRIPTION:
Mapping XS 613a842a
END DESCRIPTION:
XS GIS Cut Line= 3
      1623589.93      6931338.25      1624145.48      6931236.26
      1624370.47      6931143.23
#Sta/Elev= 30
  4369.9 1584.75  4466.6 1584.40  4505.9 1583.71  4547.9 1584.32  4669.9 1583.35
  4710.6 1581.06  4741.1 1582.08  4751.2 1579.94  4781.6 1578.79  4791.9 1577.39
  4812.2 1576.54  4832.6 1572.92  4852.9 1573.62  4873.2 1573.34  4883.4 1572.91
  4892.9 1570.78  4898.0 1571.00  4903.7 1573.74  4924.1 1574.08  4994.7 1572.35
  5007.9 1570.08  5008.2 1569.58  5011.8 1569.58  5012.1 1570.08  5018.6 1570.66
  5031.6 1574.62  5047.9 1577.74  5154.3 1577.73  5161.5 1578.31  5178.2 1577.85
#Mann=3,-1,0
  4369.9    0.05       0  5007.9    0.05       0  5012.1    0.05       0
Bank Sta=5007.9,5012.1
Exp/Cntr=0.3,0.1

Type RM Length L Ch R = 1,1125,0,0,0
BEGIN DESCRIPTION:
Deadman 19 1.0
END DESCRIPTION:
XS GIS Cut Line= 3
      1623385.95      6931474.97      1624249.65      6931318.72
      1624381.05      6931271.33
#Sta/Elev= 30
  4116.1 1587.20  4123.7 1586.52  4165.9 1585.59  4235.8 1585.30  4267.6 1584.38
  4406.4 1583.30  4465.0 1583.70  4552.1 1583.14  4643.6 1583.39  4684.0 1581.05
  4714.7 1581.27  4724.9 1582.35  4735.0 1581.68  4742.6 1579.37  4755.4 1579.16
  4785.8 1577.12  4796.0 1577.08  4806.3 1575.92  4846.8 1573.77  4913.2 1573.47
  4978.9 1571.73  5013.1 1572.10  5020.8 1571.50  5029.3 1569.58  5029.6 1569.08
  5033.2 1569.08  5033.5 1569.58  5063.3 1576.98  5074.4 1577.59  5133.5 1577.79
#Mann=3,-1,0
  4116.1    0.05       0  5029.3    0.05       0  5033.5    0.05       0
Bank Sta=5029.3,5033.5
Exp/Cntr=0.3,0.1

Chan Stop Cuts=-1