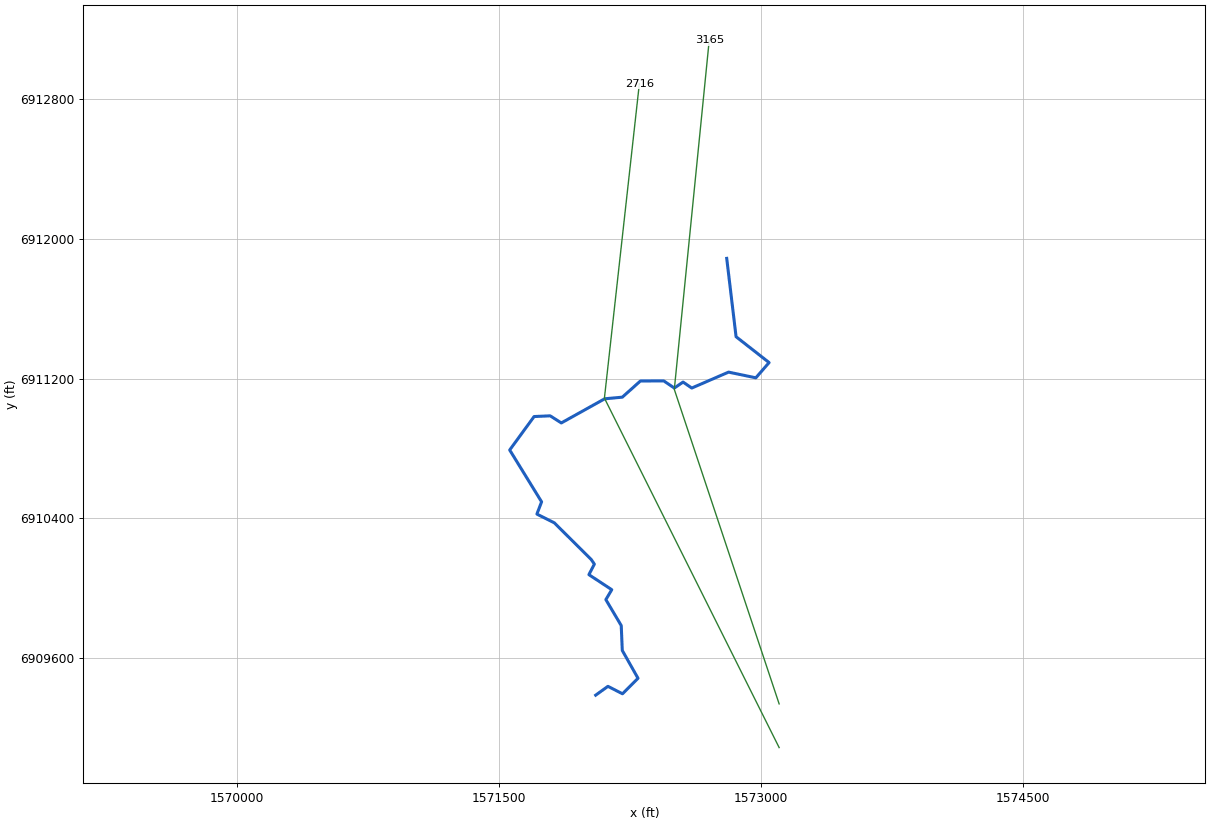
--- Deadman 20.prj (project) ---

Proj Title=Deadman 20 Base Level Engineering
Current Plan=p01
Default Exp/Contr=0.3,0.1
English Units
Geom File=g01
Flow File=f01
Plan File=p01
BEGIN DESCRIPTION:
Deadman 20
END DESCRIPTION:

--- Deadman 20.p01 (plan) ---

Plan Title=Multiple Run
Short Identifier=Multiple
Geom File=g01
Flow File=f01
Subcritical Flow
K Sum by GR= 0
Std Step Tol= 0.01
Critical Tol= 0.01
Num of Std Step Trials= 20
Max Error Tol= 0.3
Flow Tol Ratio= 0.001
Split Flow NTrial= 30
Split Flow Tol= 0.02
Split Flow Ratio= 0.02
Log Output Level= 0
Friction Slope Method= 1
Unsteady Friction Slope Method= 2
Unsteady Bridges Friction Slope Method= 1
Parabolic Critical Depth
Global Vel Dist=  1 , 1 , 1
Global Log Level= 0
CheckData=True
Encroach Param= -1, 0, 0, 0
BEGIN DESCRIPTION:
Multiple Run
END DESCRIPTION:

--- Deadman 20.f01 (steady flow) ---

Flow Title=Multiple
Number of Profiles=7
Profile Names=10-year,25-year,50-year,1pct_min,100-year,1pct_plu,500-year
River Rch & RM= Deadman 20,Reach-1,3165
     194     261     314     188     374     747     541
Boundary for River Rch & Prof#=Deadman 20,Reach-1,1
Up Type=0
Dn Type=3
Dn Slope=0.005
Boundary for River Rch & Prof#=Deadman 20,Reach-1,2
Up Type=0
Dn Type=3
Dn Slope=0.005
Boundary for River Rch & Prof#=Deadman 20,Reach-1,3
Up Type=0
Dn Type=3
Dn Slope=0.005
Boundary for River Rch & Prof#=Deadman 20,Reach-1,4
Up Type=0
Dn Type=3
Dn Slope=0.005
Boundary for River Rch & Prof#=Deadman 20,Reach-1,5
Up Type=0
Dn Type=3
Dn Slope=0.005
Boundary for River Rch & Prof#=Deadman 20,Reach-1,6
Up Type=0
Dn Type=3
Dn Slope=0.005
Boundary for River Rch & Prof#=Deadman 20,Reach-1,7
Up Type=0
Dn Type=3
Dn Slope=0.005

--- Deadman 20.g01 (geometry) ---

Geom Title=Existing Conditions

River Reach=Deadman 20,Reach-1
Reach XY= 30
      1572805.00      6911888.00      1572858.54      6911439.46
      1573047.52      6911291.56      1572971.78      6911204.29
      1572815.55      6911236.89      1572604.90      6911145.78
      1572555.00      6911179.97      1572505.10      6911145.78
      1572444.56      6911186.64      1572310.86      6911185.94
      1572207.42      6911093.54      1572106.59      6911084.17
      1571858.32      6910946.05      1571794.51      6910986.74
      1571702.56      6910982.61      1571562.84      6910791.23
      1571745.41      6910494.54      1571718.50      6910424.31
      1571818.18      6910374.37      1572029.22      6910164.66
      1572047.43      6910137.99      1572016.12      6910077.68
      1572147.11      6909991.58      1572113.25      6909934.78
      1572201.24      6909786.44      1572207.25      6909643.93
      1572297.23      6909484.56      1572208.44      6909395.80
      1572125.25      6909438.46      1572055.00      6909388.00

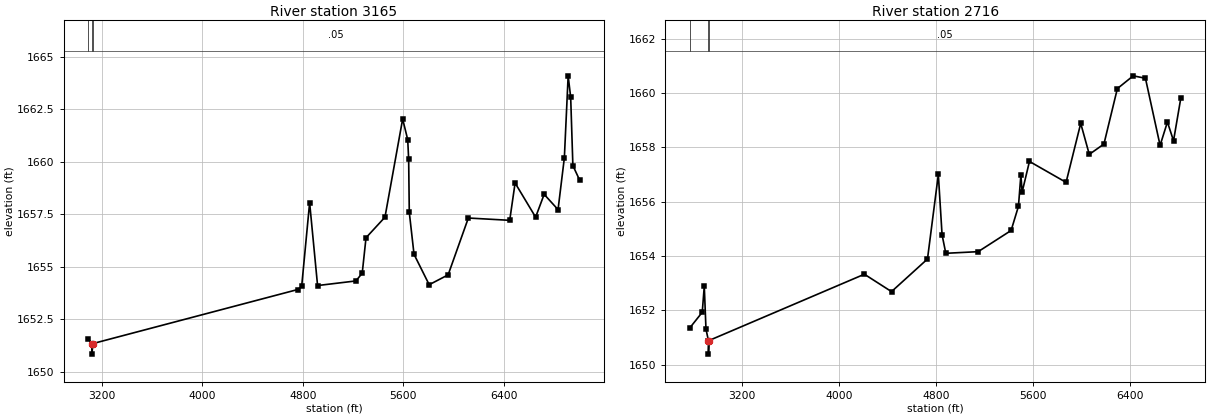
Type RM Length L Ch R = 1,3165,449,449,449
BEGIN DESCRIPTION:
Deadman 20 2.0
END DESCRIPTION:
XS GIS Cut Line= 3
      1573104.99      6909338.04      1572505.00      6911138.00
      1572705.00      6913138.00
#Sta/Elev= 30
  3094.5 1651.55  3123.9 1651.33  3124.2 1650.83  3128.3 1651.33  4759.9 1653.91
  4791.5 1654.06  4854.8 1658.05  4918.0 1654.10  5223.0 1654.32  5273.2 1654.69
  5303.4 1656.38  5454.1 1657.36  5594.8 1662.04  5635.0 1661.06  5642.6 1660.13
  5647.6 1657.59  5685.3 1655.59  5805.9 1654.14  5956.6 1654.61  6117.4 1657.32
  6446.5 1657.21  6489.3 1658.99  6652.6 1657.36  6720.4 1658.45  6831.0 1657.72
  6881.2 1660.19  6911.4 1664.10  6931.5 1663.08  6949.0 1659.82  7001.8 1659.14
#Mann=3,-1,0
  3094.5    0.05       0  3123.9    0.03       0  3128.3    0.05       0
Bank Sta=3123.9,3128.3
Exp/Cntr=0.3,0.1

Type RM Length L Ch R = 1,2716,0,0,0
BEGIN DESCRIPTION:
Deadman 20 1.0
END DESCRIPTION:
XS GIS Cut Line= 3
      1573105.02      6909087.96      1572105.00      6911088.00
      1572305.00      6912888.01
#Sta/Elev= 30
  2768.1 1651.35  2871.6 1651.93  2888.3 1652.89  2902.3 1651.31  2922.4 1650.89
  2922.8 1650.39  2926.9 1650.89  4207.6 1653.33  4431.2 1652.69  4727.5 1653.89
  4816.9 1657.00  4847.7 1654.78  4878.4 1654.10  5145.1 1654.16  5416.7 1654.94
  5477.1 1655.83  5497.2 1656.99  5507.3 1656.35  5567.7 1657.48  5869.5 1656.71
  5990.2 1658.88  6060.7 1657.74  6181.4 1658.12  6292.1 1660.16  6422.9 1660.63
  6523.5 1660.54  6644.2 1658.07  6704.6 1658.93  6754.9 1658.24  6815.3 1659.82
#Mann=3,-1,0
  2768.1    0.05       0  2922.4    0.03       0  2926.9    0.05       0
Bank Sta=2922.4,2926.9
Exp/Cntr=0.3,0.1

Chan Stop Cuts=-1