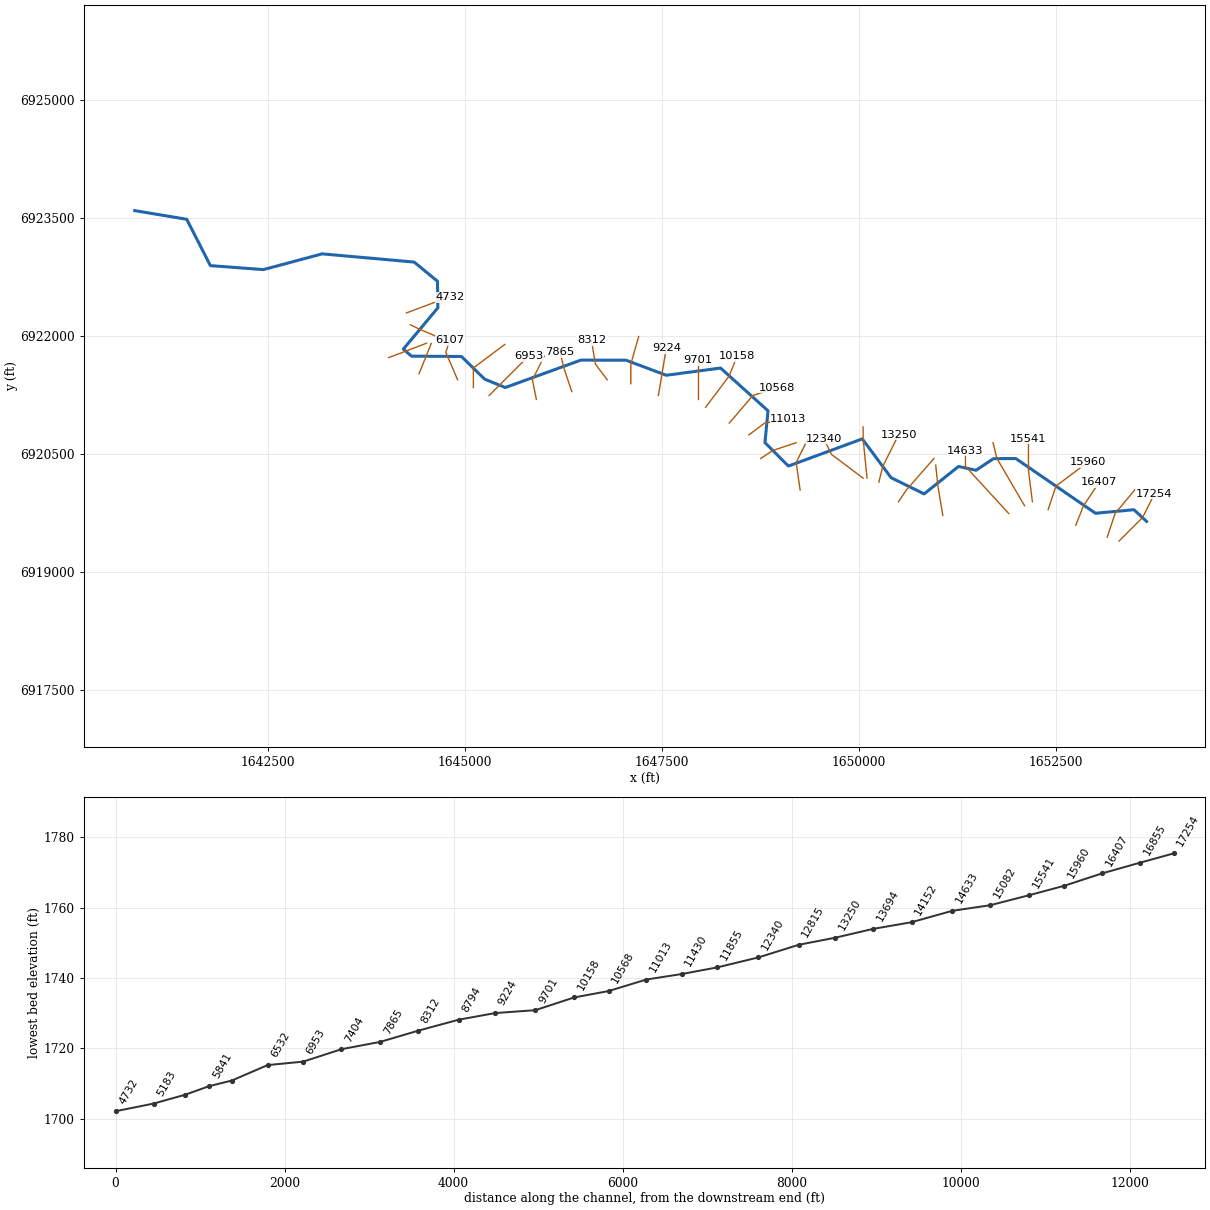
--- Deadman 21.prj (project) ---

Proj Title=Deadman 21 Base Level Engineering
Current Plan=p01
Default Exp/Contr=0.3,0.1
English Units
Geom File=g01
Flow File=f01
Plan File=p01
BEGIN DESCRIPTION:
Deadman 21
END DESCRIPTION:

--- Deadman 21.p01 (plan) ---

Plan Title=Multiple Run
Short Identifier=Multiple
Geom File=g01
Flow File=f01
Subcritical Flow
K Sum by GR= 0
Std Step Tol= 0.01
Critical Tol= 0.01
Num of Std Step Trials= 20
Max Error Tol= 0.3
Flow Tol Ratio= 0.001
Split Flow NTrial= 30
Split Flow Tol= 0.02
Split Flow Ratio= 0.02
Log Output Level= 0
Friction Slope Method= 1
Unsteady Friction Slope Method= 2
Unsteady Bridges Friction Slope Method= 1
Parabolic Critical Depth
Global Vel Dist=  1 , 1 , 1
Global Log Level= 0
CheckData=True
Encroach Param= -1, 0, 0, 0
BEGIN DESCRIPTION:
Multiple Run
END DESCRIPTION:

--- Deadman 21.f01 (steady flow) ---

Flow Title=Multiple
Number of Profiles=7
Profile Names=10-year,25-year,50-year,1pct_min,100-year,1pct_plu,500-year
River Rch & RM= Deadman 21,Reach-1,17254
     377     534     666     414     825    1646    1283
River Rch & RM= Deadman 21,Reach-1,10568
     476     680     853     532    1061    2117    1665
River Rch & RM= Deadman 21,Reach-1,4272
     554     796    1004     629    1255    2503    1986
Boundary for River Rch & Prof#=Deadman 21,Reach-1,1
Up Type=0
Dn Type=3
Dn Slope=0.005
Boundary for River Rch & Prof#=Deadman 21,Reach-1,2
Up Type=0
Dn Type=3
Dn Slope=0.005
Boundary for River Rch & Prof#=Deadman 21,Reach-1,3
Up Type=0
Dn Type=3
Dn Slope=0.005
Boundary for River Rch & Prof#=Deadman 21,Reach-1,4
Up Type=0
Dn Type=3
Dn Slope=0.005
Boundary for River Rch & Prof#=Deadman 21,Reach-1,5
Up Type=0
Dn Type=3
Dn Slope=0.005
Boundary for River Rch & Prof#=Deadman 21,Reach-1,6
Up Type=0
Dn Type=3
Dn Slope=0.005
Boundary for River Rch & Prof#=Deadman 21,Reach-1,7
Up Type=0
Dn Type=3
Dn Slope=0.005

--- Deadman 21.g01 (geometry) ---

Geom Title=Existing Conditions

River Reach=Deadman 21,Reach-1
Reach XY= 30
      1653655.00      6919638.00      1653494.52      6919786.81
      1653006.47      6919741.55      1651994.57      6920436.95
      1651710.93      6920435.76      1651489.78      6920288.25
      1651266.87      6920336.49      1650830.09      6919987.76
      1650410.62      6920193.62      1650044.56      6920686.97
      1649106.65      6920341.65      1648808.61      6920639.50
      1648847.24      6921044.17      1648244.53      6921587.07
      1647555.00      6921495.56      1647044.50      6921686.81
      1646470.39      6921687.91      1645511.11      6921339.80
      1645248.83      6921445.86      1644953.50      6921734.39
      1644320.15      6921738.38      1644215.94      6921827.98
      1644654.62      6922353.16      1644649.54      6922690.45
      1644353.42      6922934.18      1643184.85      6923038.36
      1642439.78      6922838.52      1641765.28      6922888.99
      1641465.11      6923477.62      1640805.00      6923588.00

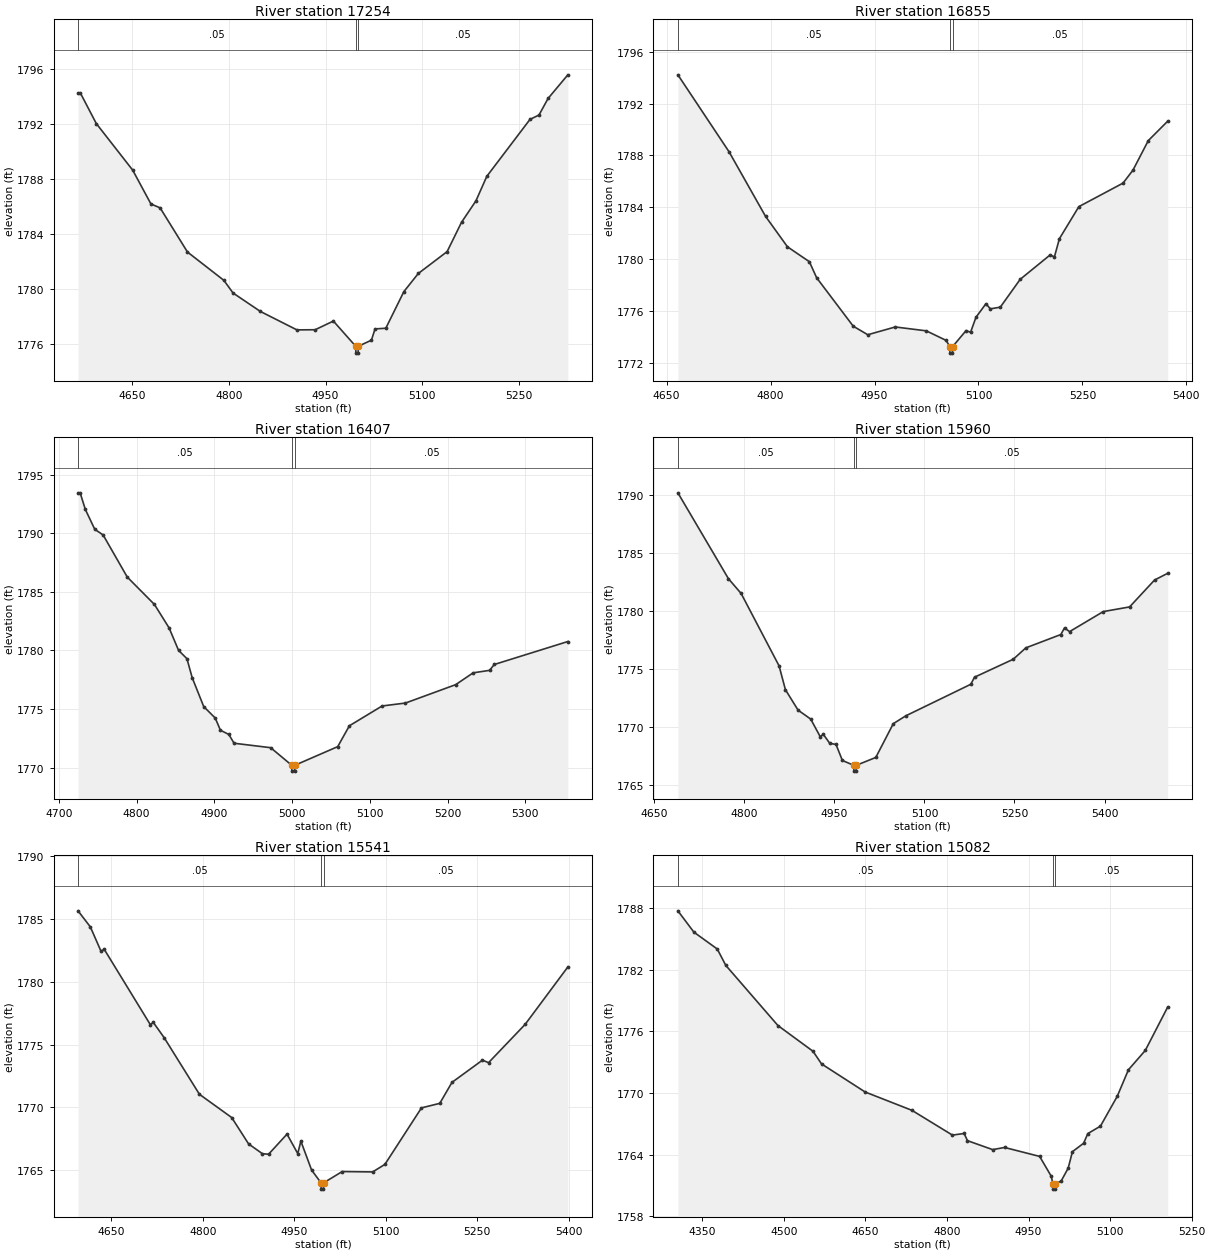
Type RM Length L Ch R = 1,17254,399,399,399
BEGIN DESCRIPTION:
Deadman 21 37.0
END DESCRIPTION:
XS GIS Cut Line= 3
      1653305.02      6919388.02      1653605.00      6919688.00
      1653754.98      6919987.96
#Sta/Elev= 30
  4566.2 1794.29  4569.7 1794.29  4594.5 1792.06  4651.0 1788.67  4679.3 1786.21
  4693.5 1785.93  4735.9 1782.72  4792.4 1780.66  4806.6 1779.74  4849.0 1778.40
  4905.6 1777.06  4933.9 1777.07  4962.2 1777.70  4996.8 1775.87  4997.1 1775.37
  5000.6 1775.37  5000.8 1775.87  5021.2 1776.31  5026.8 1777.13  5043.5 1777.18
  5071.5 1779.84  5093.9 1781.16  5138.6 1782.75  5160.9 1784.88  5183.3 1786.44
  5200.1 1788.22  5267.1 1792.36  5281.1 1792.68  5295.1 1793.88  5325.8 1795.60
#Mann=3,-1,0
  4566.2    0.05       0  4996.8    0.05       0  5000.8    0.05       0
Bank Sta=4996.8,5000.8
Exp/Cntr=0.3,0.1

Type RM Length L Ch R = 1,16855,448,448,448
BEGIN DESCRIPTION:
Deadman 21 36.0
END DESCRIPTION:
XS GIS Cut Line= 3
      1653155.01      6919438.03      1653255.00      6919738.00
      1653504.99      6920037.99
#Sta/Elev= 30
  4666.3 1794.22  4740.1 1788.28  4792.8 1783.29  4824.4 1780.94  4856.0 1779.79
  4866.5 1778.55  4919.3 1774.81  4940.3 1774.15  4979.9 1774.75  5024.8 1774.45
  5053.4 1773.71  5058.6 1773.23  5058.9 1772.73  5062.4 1772.73  5062.6 1773.23
  5082.1 1774.47  5088.6 1774.34  5096.4 1775.50  5110.7 1776.54  5117.2 1776.15
  5131.5 1776.28  5160.2 1778.43  5203.1 1780.30  5209.6 1780.17  5216.8 1781.57
  5244.8 1784.04  5308.6 1785.86  5322.9 1786.86  5345.0 1789.14  5373.0 1790.64
#Mann=3,-1,0
  4666.3    0.05       0  5058.6    0.03       0  5062.6    0.05       0
Bank Sta=5058.6,5062.6
Exp/Cntr=0.3,0.1

Type RM Length L Ch R = 1,16407,447,447,447
BEGIN DESCRIPTION:
Deadman 21 35.0
END DESCRIPTION:
XS GIS Cut Line= 3
      1652755.00      6919587.99      1652855.00      6919838.00
      1653054.99      6920137.98
#Sta/Elev= 30
  4724.8 1793.45  4727.5 1793.45  4734.2 1792.03  4746.3 1790.34  4757.1 1789.85
  4788.1 1786.26  4823.1 1783.92  4841.9 1781.92  4854.1 1780.00  4864.8 1779.30
  4871.6 1777.67  4886.4 1775.21  4901.2 1774.23  4907.9 1773.19  4918.7 1772.83
  4925.4 1772.08  4972.5 1771.70  4999.6 1770.20  4999.8 1769.70  5003.3 1769.70
  5003.6 1770.20  5058.7 1771.79  5073.7 1773.57  5115.8 1775.26  5145.8 1775.51
  5210.4 1777.08  5232.9 1778.09  5254.0 1778.30  5260.0 1778.80  5354.6 1780.76
#Mann=3,-1,0
  4724.8    0.05       0  4999.6    0.03       0  5003.6    0.05       0
Bank Sta=4999.6,5003.6
Exp/Cntr=0.3,0.1

Type RM Length L Ch R = 1,15960,419,419,419
BEGIN DESCRIPTION:
Deadman 21 34.0
END DESCRIPTION:
XS GIS Cut Line= 3
      1652405.00      6919788.01      1652505.00      6920088.00
      1652904.99      6920387.99
#Sta/Elev= 30
  4689.1 1790.19  4773.4 1782.78  4794.5 1781.51  4857.7 1775.27  4868.3 1773.21
  4889.4 1771.45  4910.4 1770.68  4926.3 1769.16  4931.5 1769.36  4942.1 1768.59
  4952.6 1768.49  4963.2 1767.11  4982.2 1766.69  4982.4 1766.19  4986.0 1766.19
  4986.3 1766.69  5018.9 1767.37  5048.0 1770.28  5068.9 1770.96  5177.2 1773.68
  5183.4 1774.29  5248.0 1775.84  5268.9 1776.82  5327.2 1777.97  5333.4 1778.54
  5341.8 1778.22  5398.0 1779.95  5441.8 1780.35  5483.4 1782.67  5505.3 1783.25
#Mann=3,-1,0
  4689.1    0.05       0  4982.2    0.03       0  4986.3    0.05       0
Bank Sta=4982.2,4986.3
Exp/Cntr=0.3,0.1

Type RM Length L Ch R = 1,15541,459,459,459
BEGIN DESCRIPTION:
Deadman 21 33.0
END DESCRIPTION:
XS GIS Cut Line= 3
      1652205.01      6919887.96      1652155.00      6920288.00
      1652155.00      6920688.04
#Sta/Elev= 30
  4595.4 1785.65  4615.6 1784.37  4633.2 1782.42  4638.3 1782.59  4713.9 1776.59
  4718.9 1776.76  4736.5 1775.56  4794.5 1771.04  4847.4 1769.19  4875.1 1767.09
  4897.8 1766.31  4907.9 1766.27  4938.1 1767.87  4955.7 1766.32  4960.8 1767.31
  4978.4 1765.01  4993.9 1763.99  4994.2 1763.49  4997.8 1763.49  4998.1 1763.99
  5028.6 1764.89  5078.6 1764.86  5098.6 1765.46  5158.6 1769.96  5188.6 1770.32
  5208.6 1771.99  5258.6 1773.76  5268.6 1773.56  5328.6 1776.61  5398.6 1781.18
#Mann=3,-1,0
  4595.4    0.05       0  4993.9    0.05       0  4998.1    0.05       0
Bank Sta=4993.9,4998.1
Exp/Cntr=0.3,0.1

Type RM Length L Ch R = 1,15082,449,449,449
BEGIN DESCRIPTION:
Deadman 21 32.0
END DESCRIPTION:
XS GIS Cut Line= 3
      1652105.01      6919837.98      1651755.00      6920438.00
      1651705.00      6920638.00
#Sta/Elev= 30
  4305.0 1787.71  4334.4 1785.64  4377.4 1784.00  4393.1 1782.41  4489.0 1776.56
  4553.5 1774.06  4569.2 1772.83  4649.4 1770.10  4735.4 1768.32  4809.9 1765.91
  4831.4 1766.07  4837.6 1765.37  4883.9 1764.50  4905.8 1764.71  4970.3 1763.84
  4991.8 1761.90  4994.6 1761.16  4994.9 1760.66  4998.6 1760.66  4998.8 1761.16
  5009.9 1761.45  5022.8 1762.70  5030.6 1764.30  5051.2 1765.12  5058.9 1766.06
  5082.1 1766.78  5113.0 1769.68  5133.6 1772.26  5164.6 1774.14  5205.8 1778.36
#Mann=3,-1,0
  4305.0    0.05       0  4994.6    0.05       0  4998.8    0.05       0
Bank Sta=4994.6,4998.8
Exp/Cntr=0.3,0.1

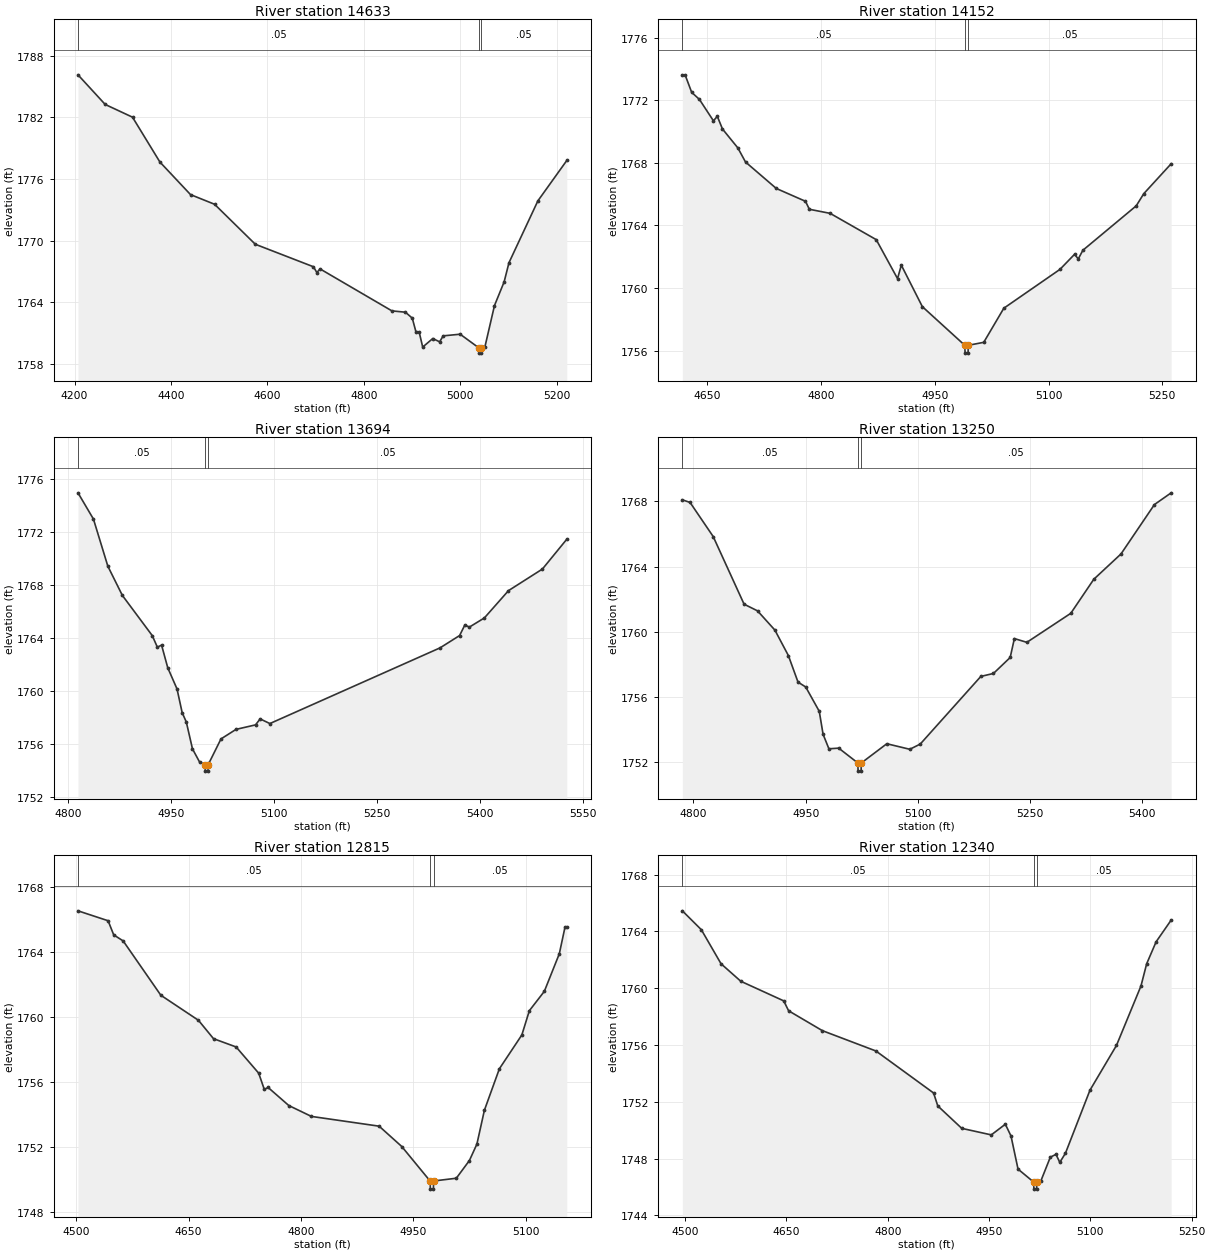
Type RM Length L Ch R = 1,14633,481,481,481
BEGIN DESCRIPTION:
Deadman 21 31.0
END DESCRIPTION:
XS GIS Cut Line= 3
      1651904.99      6919738.01      1651355.00      6920338.00
      1651355.00      6920537.97
#Sta/Elev= 30
  4207.2 1786.14  4263.6 1783.26  4320.3 1782.02  4377.1 1777.66  4440.6 1774.49
  4490.5 1773.55  4575.0 1769.66  4695.6 1767.47  4702.6 1766.91  4709.4 1767.26
  4858.3 1763.18  4886.4 1763.05  4900.6 1762.47  4908.0 1761.17  4914.8 1761.13
  4922.2 1759.66  4943.1 1760.49  4957.3 1760.17  4964.7 1760.75  4999.9 1760.91
  5039.0 1759.57  5039.3 1759.07  5043.0 1759.07  5043.3 1759.57  5051.1 1759.65
  5071.1 1763.70  5091.1 1766.00  5101.1 1767.86  5161.1 1773.88  5221.1 1777.81
#Mann=3,-1,0
  4207.2    0.05       0  5039.0    0.05       0  5043.3    0.05       0
Bank Sta=5039,5043.3
Exp/Cntr=0.3,0.1

Type RM Length L Ch R = 1,14152,458,458,458
BEGIN DESCRIPTION:
Deadman 21 30.0
END DESCRIPTION:
XS GIS Cut Line= 3
      1651067.31      6919715.82      1651005.00      6920088.00
      1650977.12      6920353.88
#Sta/Elev= 30
  4617.0 1773.62  4620.6 1773.62  4629.3 1772.50  4639.5 1772.05  4658.0 1770.68
  4663.1 1770.97  4669.9 1770.16  4690.2 1768.95  4700.3 1768.05  4740.9 1766.36
  4779.4 1765.54  4784.5 1765.03  4811.9 1764.77  4872.7 1763.09  4900.8 1760.60
  4905.8 1761.46  4933.5 1758.81  4989.5 1756.34  4989.9 1755.84  4993.8 1755.84
  4994.1 1756.34  5014.5 1756.53  5041.0 1758.71  5115.0 1761.19  5134.2 1762.15
  5139.2 1761.86  5145.2 1762.41  5215.6 1765.25  5225.6 1766.03  5261.7 1767.94
#Mann=3,-1,0
  4617.0    0.05       0  4989.5    0.03       0  4994.1    0.05       0
Bank Sta=4989.5,4994.1
Exp/Cntr=0.3,0.1

Type RM Length L Ch R = 1,13694,444,444,444
BEGIN DESCRIPTION:
Deadman 21 29.0
END DESCRIPTION:
XS GIS Cut Line= 3
      1650505.02      6919888.03      1650605.00      6920038.00
      1650954.97      6920437.96
#Sta/Elev= 30
  4814.6 1774.93  4837.1 1772.95  4858.1 1769.39  4879.2 1767.19  4922.7 1764.16
  4930.2 1763.28  4936.3 1763.44  4945.3 1761.73  4958.8 1760.13  4966.3 1758.34
  4972.3 1757.64  4981.3 1755.61  4991.8 1754.60  4999.7 1754.43  5000.0 1753.93
  5003.9 1753.93  5004.3 1754.43  5022.8 1756.36  5044.7 1757.08  5073.1 1757.42
  5079.8 1757.87  5094.0 1757.52  5341.7 1763.23  5370.2 1764.16  5377.8 1764.95
  5384.5 1764.80  5406.3 1765.49  5441.4 1767.55  5490.8 1769.18  5526.3 1771.43
#Mann=3,-1,0
  4814.6    0.05       0  4999.7    0.03       0  5004.3    0.05       0
Bank Sta=4999.7,5004.3
Exp/Cntr=0.3,0.1

Type RM Length L Ch R = 1,13250,435,435,435
BEGIN DESCRIPTION:
Deadman 21 28.0
END DESCRIPTION:
XS GIS Cut Line= 3
      1650255.00      6920137.98      1650305.00      6920338.00
      1650505.01      6920738.01
#Sta/Elev= 30
  4785.2 1768.09  4795.5 1767.93  4826.4 1765.84  4867.7 1761.69  4885.7 1761.28
  4908.9 1760.10  4926.9 1758.54  4939.8 1756.91  4950.1 1756.61  4968.2 1755.12
  4973.3 1753.71  4981.1 1752.82  4994.2 1752.86  5019.8 1751.95  5020.1 1751.45
  5024.1 1751.45  5024.4 1751.95  5058.5 1753.13  5089.2 1752.79  5103.2 1753.11
  5184.2 1757.26  5201.0 1757.44  5223.4 1758.42  5229.0 1759.58  5245.7 1759.35
  5304.4 1761.13  5335.2 1763.22  5371.5 1764.77  5416.2 1767.80  5438.6 1768.52
#Mann=3,-1,0
  4785.2    0.05       0  5019.8    0.03       0  5024.4    0.05       0
Bank Sta=5019.8,5024.4
Exp/Cntr=0.3,0.1

Type RM Length L Ch R = 1,12815,475,475,475
BEGIN DESCRIPTION:
Deadman 21 27.0
END DESCRIPTION:
XS GIS Cut Line= 3
      1650105.00      6920187.99      1650055.00      6920688.00
      1650055.00      6920838.00
#Sta/Elev= 30
  4502.3 1766.53  4542.5 1765.92  4550.0 1765.05  4562.6 1764.68  4612.9 1761.34
  4663.1 1759.80  4683.2 1758.67  4713.4 1758.16  4743.5 1756.55  4751.0 1755.55
  4756.1 1755.67  4783.7 1754.56  4813.9 1753.89  4904.3 1753.29  4934.5 1752.04
  4972.3 1749.92  4972.7 1749.42  4976.7 1749.42  4977.0 1749.92  5007.3 1750.09
  5024.8 1751.18  5034.8 1752.19  5044.8 1754.27  5064.8 1756.82  5094.8 1758.90
  5104.8 1760.39  5124.8 1761.58  5144.8 1763.89  5152.3 1765.51  5154.8 1765.51
#Mann=3,-1,0
  4502.3    0.05       0  4972.3    0.05       0  4977.0    0.05       0
Bank Sta=4972.3,4977
Exp/Cntr=0.3,0.1

Type RM Length L Ch R = 1,12340,485,485,485
BEGIN DESCRIPTION:
Deadman 21 26.0
END DESCRIPTION:
XS GIS Cut Line= 3
      1650055.01      6920187.99      1649655.00      6920488.00
      1649555.01      6920687.99
#Sta/Elev= 30
  4496.0 1765.45  4524.1 1764.12  4553.3 1761.72  4582.5 1760.49  4646.0 1759.11
  4653.3 1758.41  4703.3 1757.01  4782.5 1755.58  4867.9 1752.62  4874.1 1751.71
  4909.6 1750.13  4953.3 1749.67  4974.1 1750.42  4982.5 1749.59  4992.9 1747.26
  5016.0 1746.35  5016.4 1745.85  5020.4 1745.85  5020.7 1746.35  5026.8 1746.44
  5040.7 1748.10  5049.1 1748.30  5054.7 1747.73  5063.1 1748.38  5099.4 1752.82
  5138.6 1755.97  5174.9 1760.16  5183.3 1761.72  5197.3 1763.27  5219.6 1764.80
#Mann=3,-1,0
  4496.0    0.05       0  5016.0    0.05       0  5020.7    0.05       0
Bank Sta=5016,5020.7
Exp/Cntr=0.3,0.1

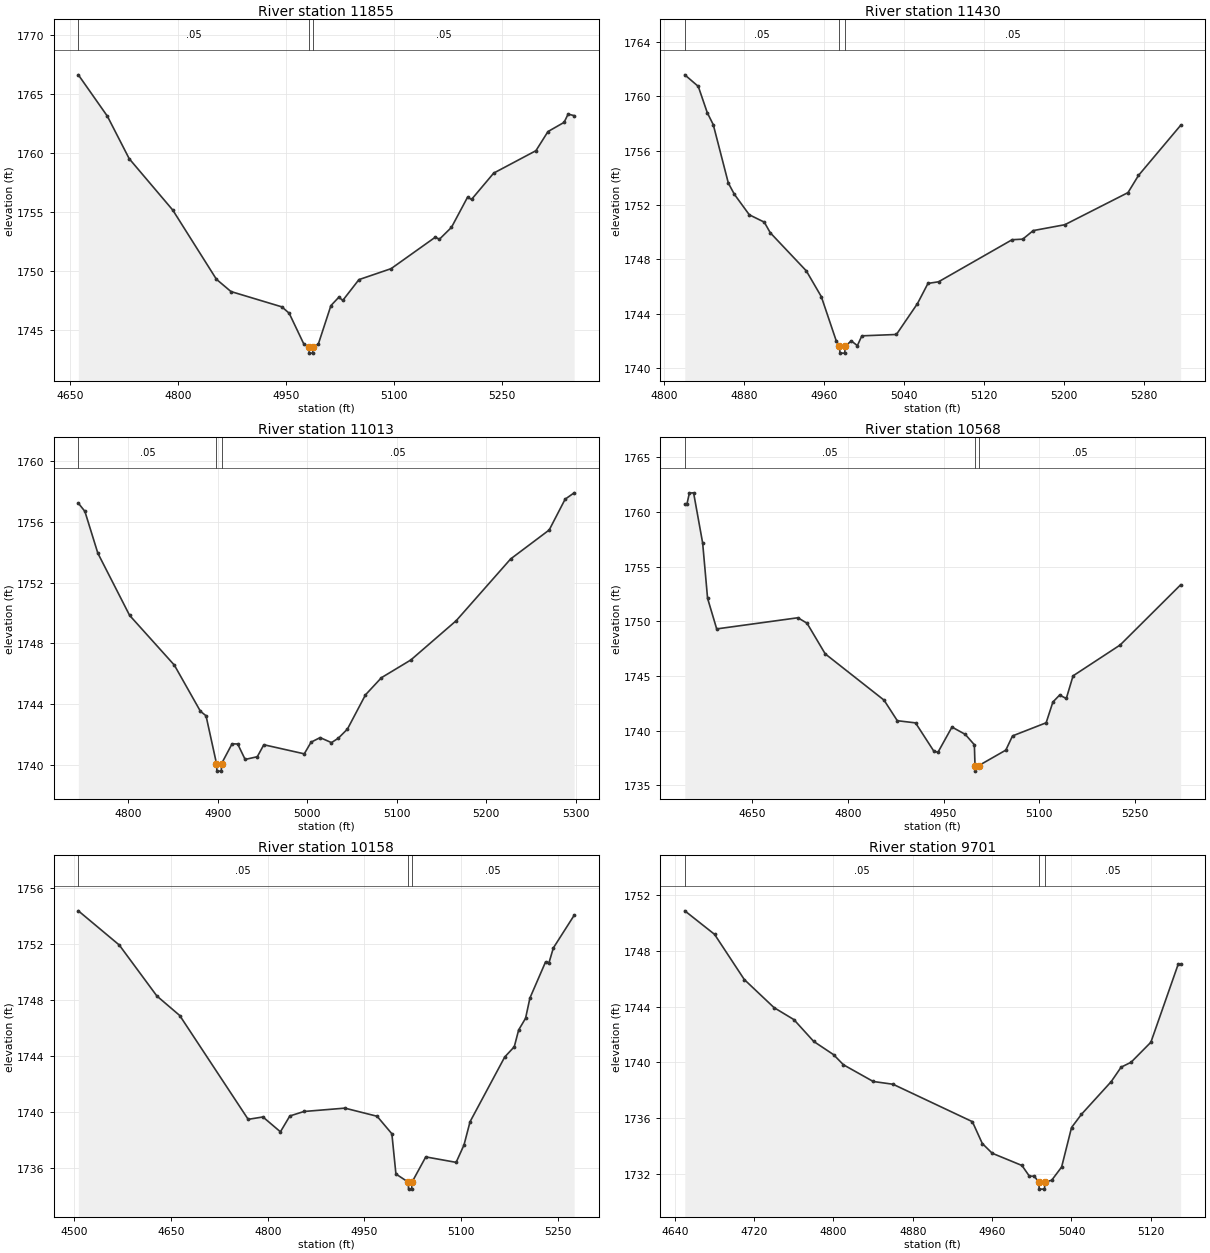
Type RM Length L Ch R = 1,11855,425,425,425
BEGIN DESCRIPTION:
Deadman 21 25.0
END DESCRIPTION:
XS GIS Cut Line= 3
      1649255.00      6920037.99      1649205.00      6920388.00
      1649355.01      6920688.02
#Sta/Elev= 30
  4661.7 1766.62  4702.1 1763.11  4732.4 1759.51  4793.0 1755.15  4853.6 1749.29
  4873.8 1748.25  4944.6 1746.95  4954.7 1746.41  4974.9 1743.82  4982.2 1743.53
  4982.6 1743.03  4987.3 1743.03  4987.8 1743.53  4995.1 1743.78  5012.7 1747.06
  5023.7 1747.77  5029.2 1747.50  5051.6 1749.26  5096.3 1750.19  5157.8 1752.86
  5163.4 1752.68  5180.2 1753.69  5202.5 1756.24  5208.1 1756.06  5238.9 1758.29
  5297.6 1760.19  5314.3 1761.81  5336.7 1762.59  5342.3 1763.29  5350.7 1763.16
#Mann=3,-1,0
  4661.7    0.05       0  4982.2    0.05       0  4987.8    0.05       0
Bank Sta=4982.2,4987.8
Exp/Cntr=0.3,0.1

Type RM Length L Ch R = 1,11430,417,417,417
BEGIN DESCRIPTION:
Deadman 21 24.0
END DESCRIPTION:
XS GIS Cut Line= 3
      1648755.01      6920438.01      1648905.00      6920538.00
      1649205.00      6920638.00
#Sta/Elev= 30
  4820.4 1761.56  4833.9 1760.71  4842.9 1758.78  4848.9 1757.90  4864.0 1753.61
  4870.0 1752.79  4885.0 1751.28  4900.0 1750.74  4906.0 1749.96  4942.1 1747.16
  4957.1 1745.27  4972.1 1742.01  4975.3 1741.62  4975.8 1741.12  4980.5 1741.12
  4981.0 1741.62  4987.1 1742.02  4993.2 1741.67  4997.7 1742.39  5032.3 1742.49
  5053.4 1744.76  5063.9 1746.24  5074.5 1746.36  5148.2 1749.45  5158.8 1749.49
  5169.3 1750.12  5200.9 1750.55  5264.2 1752.91  5274.7 1754.17  5316.9 1757.85
#Mann=3,-1,0
  4820.4    0.05       0  4975.3    0.03       0  4981.0    0.05       0
Bank Sta=4975.3,4981
Exp/Cntr=0.3,0.1

Type RM Length L Ch R = 1,11013,445,445,445
BEGIN DESCRIPTION:
Deadman 21 23.0
END DESCRIPTION:
XS GIS Cut Line= 3
      1648605.02      6920738.02      1648805.00      6920888.00
      1649104.99      6920938.00
#Sta/Elev= 30
  4744.1 1757.24  4751.4 1756.70  4765.9 1753.94  4801.4 1749.84  4851.4 1746.56
  4880.5 1743.52  4886.8 1743.22  4898.5 1740.07  4899.0 1739.57  4903.8 1739.57
  4904.2 1740.07  4915.9 1741.37  4922.2 1741.36  4930.5 1740.34  4944.1 1740.52
  4951.4 1741.31  4996.6 1740.71  5004.2 1741.48  5014.3 1741.78  5027.0 1741.45
  5034.6 1741.74  5044.8 1742.34  5065.0 1744.60  5082.8 1745.73  5115.7 1746.90
  5166.4 1749.49  5227.2 1753.56  5270.3 1755.47  5288.1 1757.50  5298.2 1757.92
#Mann=3,-1,0
  4744.1    0.05       0  4898.5    0.05       0  4904.2    0.05       0
Bank Sta=4898.5,4904.2
Exp/Cntr=0.3,0.1

Type RM Length L Ch R = 1,10568,410,410,410
BEGIN DESCRIPTION:
Deadman 21 22.0
END DESCRIPTION:
XS GIS Cut Line= 3
      1648354.98      6920887.98      1648655.00      6921238.00
      1648954.97      6921337.99
#Sta/Elev= 30
  4544.3 1760.71  4547.6 1760.71  4551.5 1761.73  4558.1 1761.75  4572.3 1757.16
  4580.0 1752.11  4594.3 1749.31  4721.6 1750.33  4735.9 1749.83  4764.4 1747.03
  4856.6 1742.80  4877.4 1740.92  4906.0 1740.72  4934.5 1738.15  4941.1 1738.03
  4963.1 1740.34  4983.9 1739.67  4998.2 1738.72  4999.2 1736.81  4999.6 1736.31
  5004.9 1736.81  5047.5 1738.23  5058.0 1739.53  5110.7 1740.73  5121.3 1742.63
  5131.8 1743.26  5142.3 1742.95  5152.9 1745.02  5226.7 1747.84  5321.5 1753.34
#Mann=3,-1,0
  4544.3    0.05       0  4999.2    0.05       0  5004.9    0.05       0
Bank Sta=4999.2,5004.9
Exp/Cntr=0.3,0.1

Type RM Length L Ch R = 1,10158,457,457,457
BEGIN DESCRIPTION:
Deadman 21 21.0
END DESCRIPTION:
XS GIS Cut Line= 3
      1648055.01      6921088.02      1648355.00      6921488.00
      1648454.99      6921737.97
#Sta/Elev= 30
  4506.1 1754.34  4569.6 1751.90  4628.0 1748.26  4663.4 1746.87  4769.6 1739.46
  4792.5 1739.63  4819.6 1738.57  4834.2 1739.70  4856.1 1740.02  4919.6 1740.26
  4969.6 1739.68  4992.5 1738.43  4998.8 1735.56  5017.9 1734.98  5018.4 1734.48
  5023.3 1734.48  5023.8 1734.98  5045.1 1736.78  5092.2 1736.39  5104.4 1737.63
  5113.8 1739.29  5167.6 1743.91  5182.4 1744.64  5189.2 1745.84  5199.9 1746.67
  5206.7 1748.12  5230.9 1750.69  5236.3 1750.64  5243.0 1751.69  5275.3 1754.02
#Mann=3,-1,0
  4506.1    0.05       0  5017.9    0.05       0  5023.8    0.05       0
Bank Sta=5017.9,5023.8
Exp/Cntr=0.3,0.1

Type RM Length L Ch R = 1,9701,477,477,477
BEGIN DESCRIPTION:
Deadman 21 20.0
END DESCRIPTION:
XS GIS Cut Line= 3
      1647955.00      6921187.97      1647955.00      6921538.00
      1647955.00      6921687.97
#Sta/Elev= 30
  4650.1 1750.89  4680.1 1749.20  4710.1 1745.95  4740.1 1743.93  4760.1 1743.07
  4780.1 1741.50  4800.1 1740.55  4810.1 1739.82  4840.1 1738.62  4860.1 1738.42
  4940.1 1735.73  4950.1 1734.16  4960.1 1733.46  4990.1 1732.58  4997.6 1731.81
  5002.6 1731.81  5007.0 1731.38  5007.5 1730.88  5012.8 1730.88  5013.3 1731.38
  5020.1 1731.52  5030.1 1732.47  5040.1 1735.31  5050.1 1736.26  5080.1 1738.61
  5090.1 1739.65  5100.1 1740.00  5120.1 1741.44  5147.6 1747.04  5150.1 1747.04
#Mann=3,-1,0
  4650.1    0.05       0  5007.0    0.05       0  5013.3    0.05       0
Bank Sta=5007,5013.3
Exp/Cntr=0.3,0.1

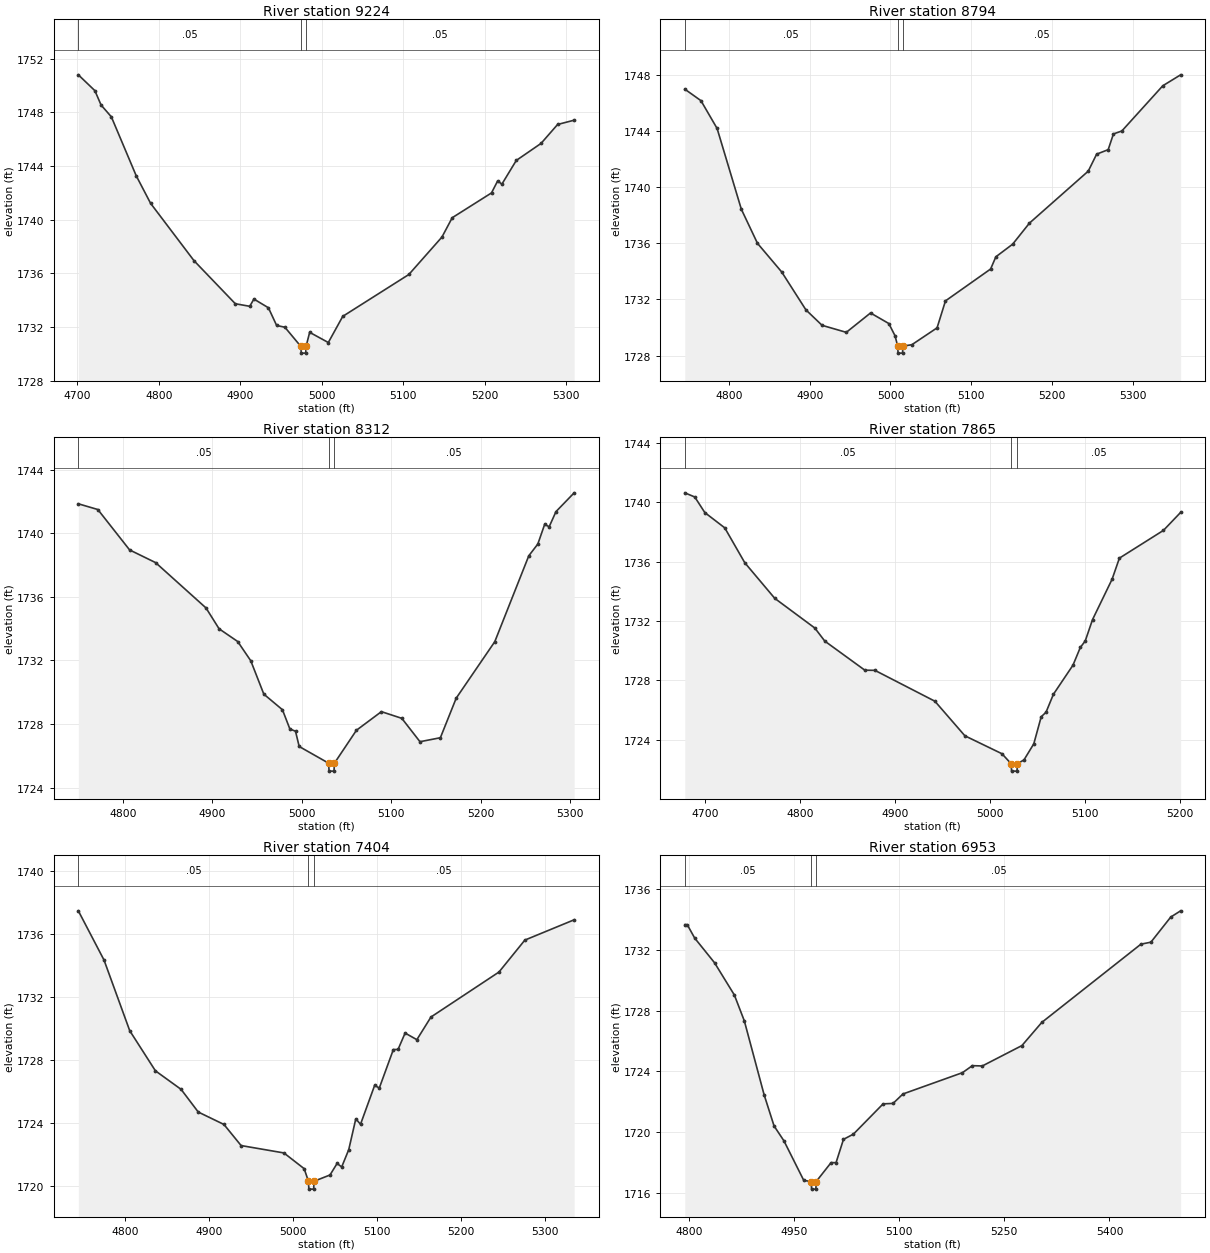
Type RM Length L Ch R = 1,9224,430,430,430
BEGIN DESCRIPTION:
Deadman 21 19.0
END DESCRIPTION:
XS GIS Cut Line= 3
      1647455.00      6921238.01      1647505.00      6921538.00
      1647555.01      6921838.04
#Sta/Elev= 30
  4701.2 1750.79  4721.5 1749.61  4729.1 1748.54  4741.7 1747.66  4772.2 1743.27
  4789.9 1741.21  4843.1 1736.94  4893.8 1733.73  4911.5 1733.54  4916.6 1734.08
  4934.4 1733.43  4944.5 1732.11  4954.6 1731.98  4974.2 1730.55  4974.7 1730.05
  4980.1 1730.05  4980.6 1730.55  4985.0 1731.60  5007.9 1730.84  5025.6 1732.79
  5106.7 1735.91  5147.3 1738.70  5159.9 1740.14  5208.1 1741.99  5215.7 1742.89
  5220.8 1742.64  5238.5 1744.41  5268.9 1745.68  5289.2 1747.09  5309.5 1747.41
#Mann=3,-1,0
  4701.2    0.05       0  4974.2    0.03       0  4980.6    0.05       0
Bank Sta=4974.2,4980.6
Exp/Cntr=0.3,0.1

Type RM Length L Ch R = 1,8794,482,482,482
BEGIN DESCRIPTION:
Deadman 21 18.0
END DESCRIPTION:
XS GIS Cut Line= 3
      1647105.00      6921388.03      1647105.00      6921638.00
      1647205.01      6921988.02
#Sta/Elev= 30
  4745.3 1746.98  4765.3 1746.16  4785.3 1744.18  4815.3 1738.43  4835.3 1736.00
  4865.3 1733.96  4895.3 1731.26  4915.3 1730.16  4945.3 1729.66  4975.3 1731.04
  4997.9 1730.29  5005.7 1729.41  5008.9 1728.68  5009.4 1728.18  5014.9 1728.18
  5015.4 1728.68  5026.5 1728.78  5057.7 1729.98  5068.1 1731.90  5124.0 1734.17
  5130.5 1735.04  5151.3 1735.94  5172.1 1737.44  5244.9 1741.14  5255.3 1742.35
  5269.6 1742.67  5276.1 1743.79  5286.5 1744.00  5337.2 1747.22  5359.3 1748.00
#Mann=3,-1,0
  4745.3    0.05       0  5008.9    0.05       0  5015.4    0.05       0
Bank Sta=5008.9,5015.4
Exp/Cntr=0.3,0.1

Type RM Length L Ch R = 1,8312,447,447,447
BEGIN DESCRIPTION:
Deadman 21 17.0
END DESCRIPTION:
XS GIS Cut Line= 3
      1646804.98      6921438.03      1646655.00      6921638.00
      1646605.00      6921938.00
#Sta/Elev= 30
  4750.3 1741.85  4772.1 1741.49  4807.6 1738.95  4836.7 1738.15  4893.0 1735.30
  4907.6 1733.99  4928.4 1733.19  4943.0 1731.98  4957.6 1729.88  4978.4 1728.90
  4986.7 1727.69  4993.0 1727.55  4997.1 1726.59  5030.0 1725.54  5030.5 1725.04
  5036.0 1725.04  5036.5 1725.54  5061.1 1727.61  5089.0 1728.78  5111.8 1728.36
  5132.1 1726.89  5154.9 1727.14  5172.6 1729.63  5215.7 1733.18  5253.7 1738.58
  5263.8 1739.32  5271.4 1740.55  5276.5 1740.41  5284.1 1741.36  5304.4 1742.54
#Mann=3,-1,0
  4750.3    0.05       0  5030.0    0.05       0  5036.5    0.05       0
Bank Sta=5030,5036.5
Exp/Cntr=0.3,0.1

Type RM Length L Ch R = 1,7865,461,461,461
BEGIN DESCRIPTION:
Deadman 21 16.0
END DESCRIPTION:
XS GIS Cut Line= 3
      1646354.99      6921288.02      1646255.00      6921588.00
      1646204.99      6921788.04
#Sta/Elev= 30
  4678.7 1740.63  4689.2 1740.35  4699.8 1739.30  4720.8 1738.27  4741.9 1735.92
  4773.5 1733.52  4815.7 1731.52  4826.2 1730.64  4868.4 1728.68  4879.0 1728.67
  4942.2 1726.59  4973.8 1724.26  5012.9 1723.05  5022.5 1722.38  5023.0 1721.88
  5028.7 1721.88  5029.2 1722.38  5036.1 1722.64  5046.4 1723.72  5054.2 1725.54
  5059.3 1725.85  5067.1 1727.06  5087.7 1729.02  5095.4 1730.21  5100.6 1730.65
  5108.3 1732.09  5128.9 1734.81  5136.6 1736.23  5183.0 1738.10  5201.1 1739.31
#Mann=3,-1,0
  4678.7    0.05       0  5022.5    0.05       0  5029.2    0.05       0
Bank Sta=5022.5,5029.2
Exp/Cntr=0.3,0.1

Type RM Length L Ch R = 1,7404,451,451,451
BEGIN DESCRIPTION:
Deadman 21 15.0
END DESCRIPTION:
XS GIS Cut Line= 3
      1645905.00      6921188.00      1645855.00      6921438.00
      1646005.02      6921738.04
#Sta/Elev= 30
  4744.2 1737.48  4774.8 1734.35  4805.4 1729.86  4836.0 1727.31  4866.6 1726.13
  4887.0 1724.69  4917.6 1723.90  4938.0 1722.56  4989.0 1722.09  5013.1 1721.09
  5018.2 1720.29  5018.7 1719.79  5024.4 1719.79  5024.9 1720.29  5043.9 1720.69
  5052.3 1721.42  5057.8 1721.20  5066.2 1722.30  5074.6 1724.26  5080.2 1723.91
  5097.0 1726.38  5102.6 1726.22  5119.3 1728.66  5124.9 1728.67  5133.3 1729.71
  5147.3 1729.29  5164.1 1730.73  5245.1 1733.59  5275.9 1735.62  5334.6 1736.91
#Mann=3,-1,0
  4744.2    0.05       0  5018.2    0.05       0  5024.9    0.05       0
Bank Sta=5018.2,5024.9
Exp/Cntr=0.3,0.1

Type RM Length L Ch R = 1,6953,421,421,421
BEGIN DESCRIPTION:
Deadman 21 14.0
END DESCRIPTION:
XS GIS Cut Line= 3
      1645305.00      6921238.00      1645455.00      6921388.00
      1645805.00      6921738.00
#Sta/Elev= 30
  4794.4 1733.64  4797.9 1733.64  4808.5 1732.76  4836.8 1731.14  4865.1 1729.02
  4879.3 1727.32  4907.5 1722.47  4921.7 1720.42  4935.8 1719.44  4964.1 1716.84
  4974.7 1716.77  4975.2 1716.27  4981.3 1716.27  4981.8 1716.77  5003.0 1718.01
  5010.1 1718.01  5020.7 1719.54  5034.8 1719.88  5077.2 1721.87  5091.4 1721.90
  5105.5 1722.52  5190.4 1723.92  5204.5 1724.38  5218.7 1724.36  5275.2 1725.70
  5303.5 1727.22  5444.9 1732.36  5459.1 1732.49  5487.4 1734.14  5501.5 1734.55
#Mann=3,-1,0
  4794.4    0.05       0  4974.7    0.03       0  4981.8    0.05       0
Bank Sta=4974.7,4981.8
Exp/Cntr=0.3,0.1

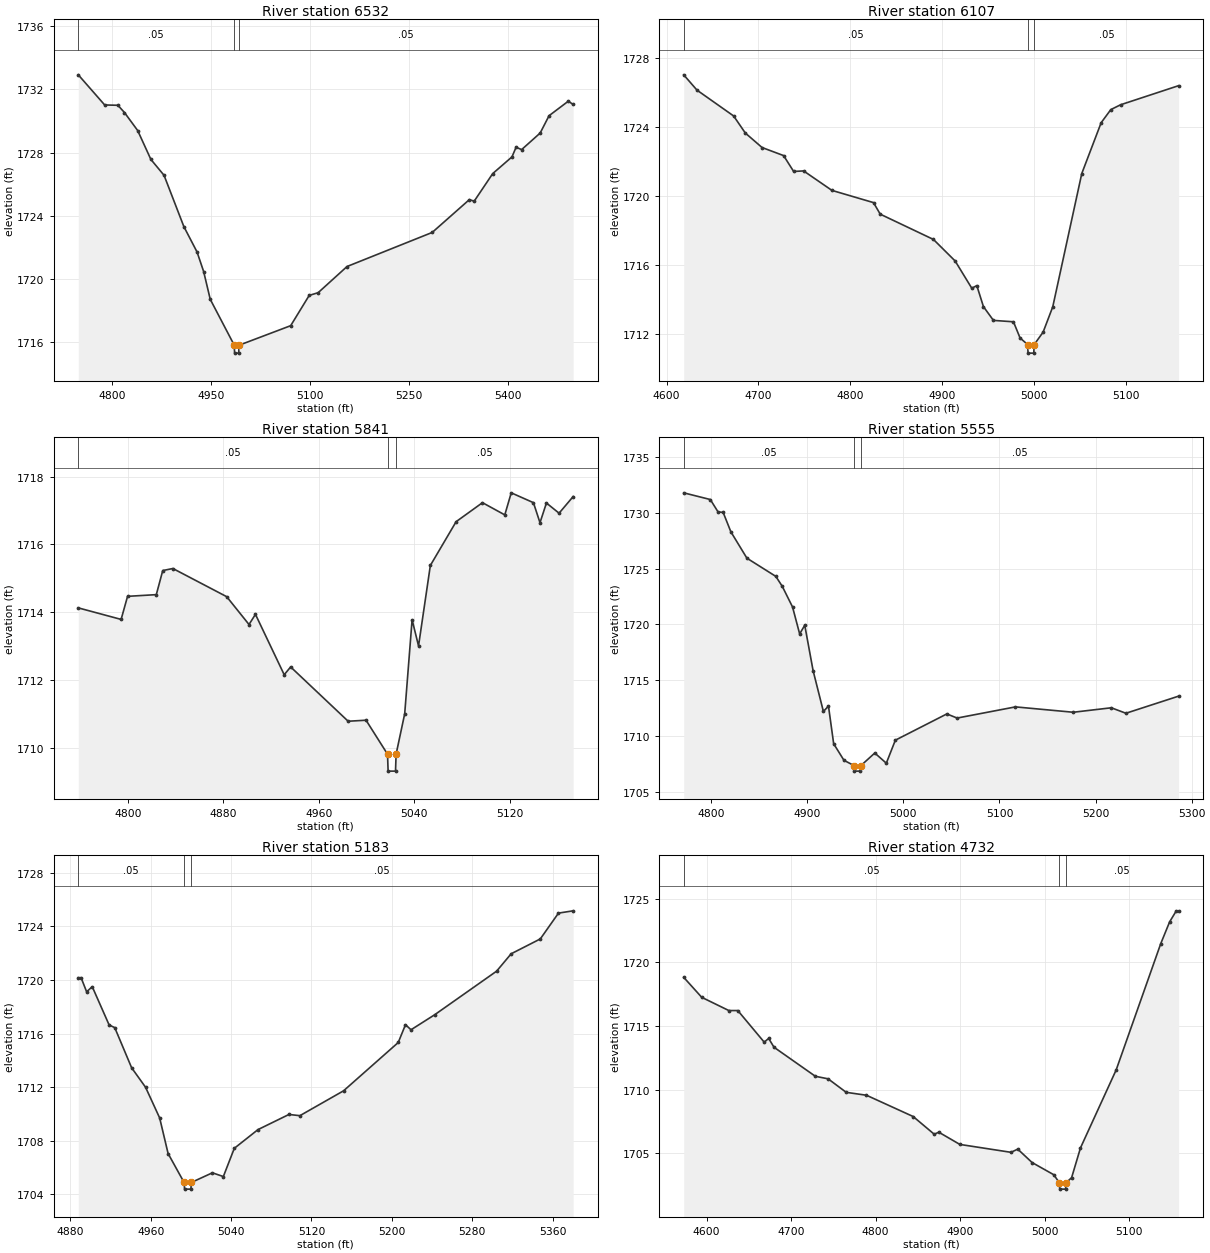
Type RM Length L Ch R = 1,6532,425,425,425
BEGIN DESCRIPTION:
Deadman 21 13.0
END DESCRIPTION:
XS GIS Cut Line= 3
      1645105.00      6921338.01      1645105.00      6921588.00
      1645505.01      6921888.01
#Sta/Elev= 30
  4749.2 1732.93  4789.2 1731.02  4809.2 1731.00  4819.2 1730.54  4839.2 1729.40
  4859.2 1727.57  4879.2 1726.56  4909.2 1723.31  4929.2 1721.70  4939.2 1720.46
  4949.2 1718.70  4985.6 1715.79  4986.1 1715.29  4992.3 1715.29  4992.8 1715.79
  5071.1 1717.03  5099.2 1718.95  5112.7 1719.12  5156.5 1720.78  5285.6 1722.94
  5341.9 1725.02  5349.2 1724.92  5377.3 1726.67  5406.5 1727.73  5412.7 1728.34
  5421.1 1728.19  5449.2 1729.24  5462.7 1730.34  5491.9 1731.26  5499.2 1731.05
#Mann=3,-1,0
  4749.2    0.05       0  4985.6    0.05       0  4992.8    0.05       0
Bank Sta=4985.6,4992.8
Exp/Cntr=0.3,0.1

Type RM Length L Ch R = 1,6107,266,266,266
BEGIN DESCRIPTION:
Deadman 21 12.0
END DESCRIPTION:
XS GIS Cut Line= 3
      1644905.01      6921437.97      1644755.00      6921788.00
      1644804.99      6921937.97
#Sta/Elev= 30
  4618.7 1727.05  4633.2 1726.16  4673.1 1724.66  4685.8 1723.67  4704.0 1722.83
  4727.5 1722.36  4738.4 1721.44  4749.3 1721.47  4780.1 1720.34  4825.4 1719.63
  4832.7 1718.96  4890.7 1717.49  4914.3 1716.24  4932.4 1714.66  4937.9 1714.81
  4945.1 1713.59  4956.0 1712.79  4977.8 1712.71  4985.0 1711.77  4993.2 1711.39
  4993.7 1710.89  4999.9 1710.89  5000.4 1711.39  5010.1 1712.11  5020.6 1713.58
  5052.2 1721.32  5073.3 1724.27  5083.8 1725.03  5094.4 1725.31  5157.6 1726.42
#Mann=3,-1,0
  4618.7    0.05       0  4993.2    0.03       0  5000.4    0.05       0
Bank Sta=4993.2,5000.4
Exp/Cntr=0.3,0.1

Type RM Length L Ch R = 1,5841,286,286,286
BEGIN DESCRIPTION:
Mapping XS a2c4b9ef
END DESCRIPTION:
XS GIS Cut Line= 2
      1644414.55      6921514.49      1644570.39      6921898.90
#Sta/Elev= 30
  4758.3 1714.13  4794.2 1713.79  4799.6 1714.47  4823.7 1714.52  4829.1 1715.23
  4837.6 1715.29  4882.7 1714.46  4901.4 1713.64  4906.8 1713.94  4930.9 1712.16
  4936.3 1712.39  4984.5 1710.79  4999.5 1710.82  5017.5 1709.82  5018.0 1709.32
  5024.2 1709.32  5024.7 1709.82  5031.9 1711.01  5038.1 1713.78  5043.5 1713.01
  5053.4 1715.38  5075.0 1716.67  5097.1 1717.23  5115.8 1716.87  5121.2 1717.52
  5139.8 1717.23  5145.3 1716.64  5150.7 1717.22  5161.3 1716.92  5173.1 1717.41
#Mann=3,-1,0
  4758.3    0.05       0  5017.5    0.03       0  5024.7    0.05       0
Bank Sta=5017.5,5024.7
Exp/Cntr=0.3,0.1

Type RM Length L Ch R = 1,5555,372,372,372
BEGIN DESCRIPTION:
Mapping XS f53fc35c
END DESCRIPTION:
XS GIS Cut Line= 2
      1644029.11      6921719.31      1644510.41      6921902.82
#Sta/Elev= 30
  4771.3 1731.78  4799.0 1731.18  4807.0 1730.08  4812.4 1730.02  4820.4 1728.29
  4837.1 1725.93  4867.2 1724.30  4873.9 1723.41  4884.6 1721.56  4892.0 1719.15
  4897.3 1719.93  4906.0 1715.86  4916.7 1712.21  4922.0 1712.69  4927.4 1709.32
  4938.1 1707.84  4948.5 1707.37  4949.0 1706.87  4955.3 1706.87  4955.8 1707.37
  4970.2 1708.49  4982.2 1707.58  4991.6 1709.64  5045.2 1711.99  5055.9 1711.62
  5116.6 1712.62  5176.8 1712.14  5216.4 1712.54  5231.6 1712.05  5286.4 1713.58
#Mann=3,-1,0
  4771.3    0.05       0  4948.5    0.03       0  4955.8    0.05       0
Bank Sta=4948.5,4955.8
Exp/Cntr=0.3,0.1

Type RM Length L Ch R = 1,5183,451,451,451
BEGIN DESCRIPTION:
Deadman 21 11.0
END DESCRIPTION:
XS GIS Cut Line= 3
      1644305.03      6922137.98      1644405.00      6922088.00
      1644755.04      6921937.98
#Sta/Elev= 30
  4887.9 1720.17  4890.7 1720.17  4896.2 1719.12  4901.8 1719.50  4918.6 1716.64
  4924.2 1716.44  4941.0 1713.44  4954.9 1711.98  4968.9 1709.69  4977.3 1707.03
  4993.2 1704.87  4993.7 1704.37  5000.0 1704.37  5000.5 1704.87  5021.4 1705.59
  5032.3 1705.31  5043.2 1707.42  5066.8 1708.82  5097.6 1709.95  5108.5 1709.86
  5152.0 1711.72  5206.4 1715.33  5213.6 1716.66  5219.1 1716.28  5242.6 1717.40
  5304.3 1720.66  5318.8 1721.96  5347.8 1723.07  5365.9 1725.00  5380.5 1725.17
#Mann=3,-1,0
  4887.9    0.05       0  4993.2    0.03       0  5000.5    0.05       0
Bank Sta=4993.2,5000.5
Exp/Cntr=0.3,0.1

Type RM Length L Ch R = 1,4732,460,460,460
BEGIN DESCRIPTION:
Deadman 21 10.0
END DESCRIPTION:
XS GIS Cut Line= 3
      1644255.03      6922288.01      1644655.00      6922438.00
      1644805.02      6922488.01
#Sta/Elev= 30
  4573.0 1718.82  4594.3 1717.25  4626.4 1716.21  4637.0 1716.21  4668.2 1713.73
  4673.5 1714.02  4679.8 1713.33  4728.7 1711.05  4743.8 1710.85  4765.2 1709.79
  4789.2 1709.56  4844.4 1707.89  4869.3 1706.50  4874.7 1706.66  4899.6 1705.70
  4960.1 1705.08  4968.1 1705.33  4985.0 1704.28  5010.7 1703.32  5017.3 1702.69
  5017.8 1702.19  5024.7 1702.19  5025.2 1702.69  5031.8 1703.09  5042.3 1705.43
  5084.5 1711.55  5137.2 1721.46  5147.7 1723.17  5155.6 1724.04  5158.3 1724.04
#Mann=3,-1,0
  4573.0    0.05       0  5017.3    0.05       0  5025.2    0.05       0
Bank Sta=5017.3,5025.2
Exp/Cntr=0.3,0.1