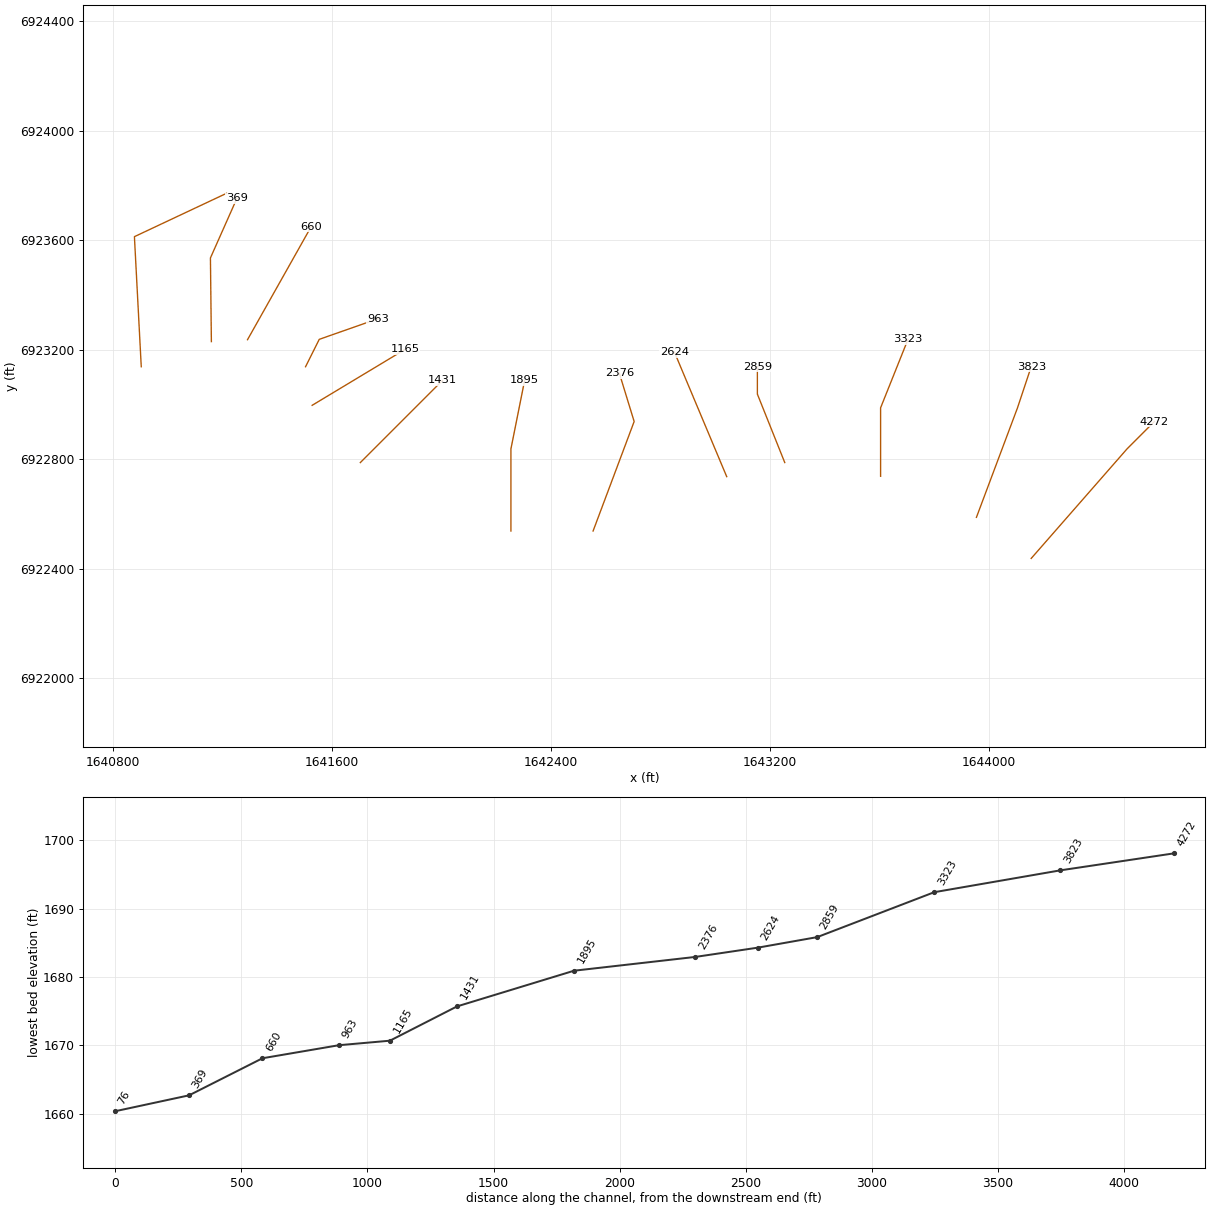
HEC-RAS study Deadman 21.prj: Deadman 21 Base Level Engineering

--- Deadman 21.g01 (geometry) --- (continued)

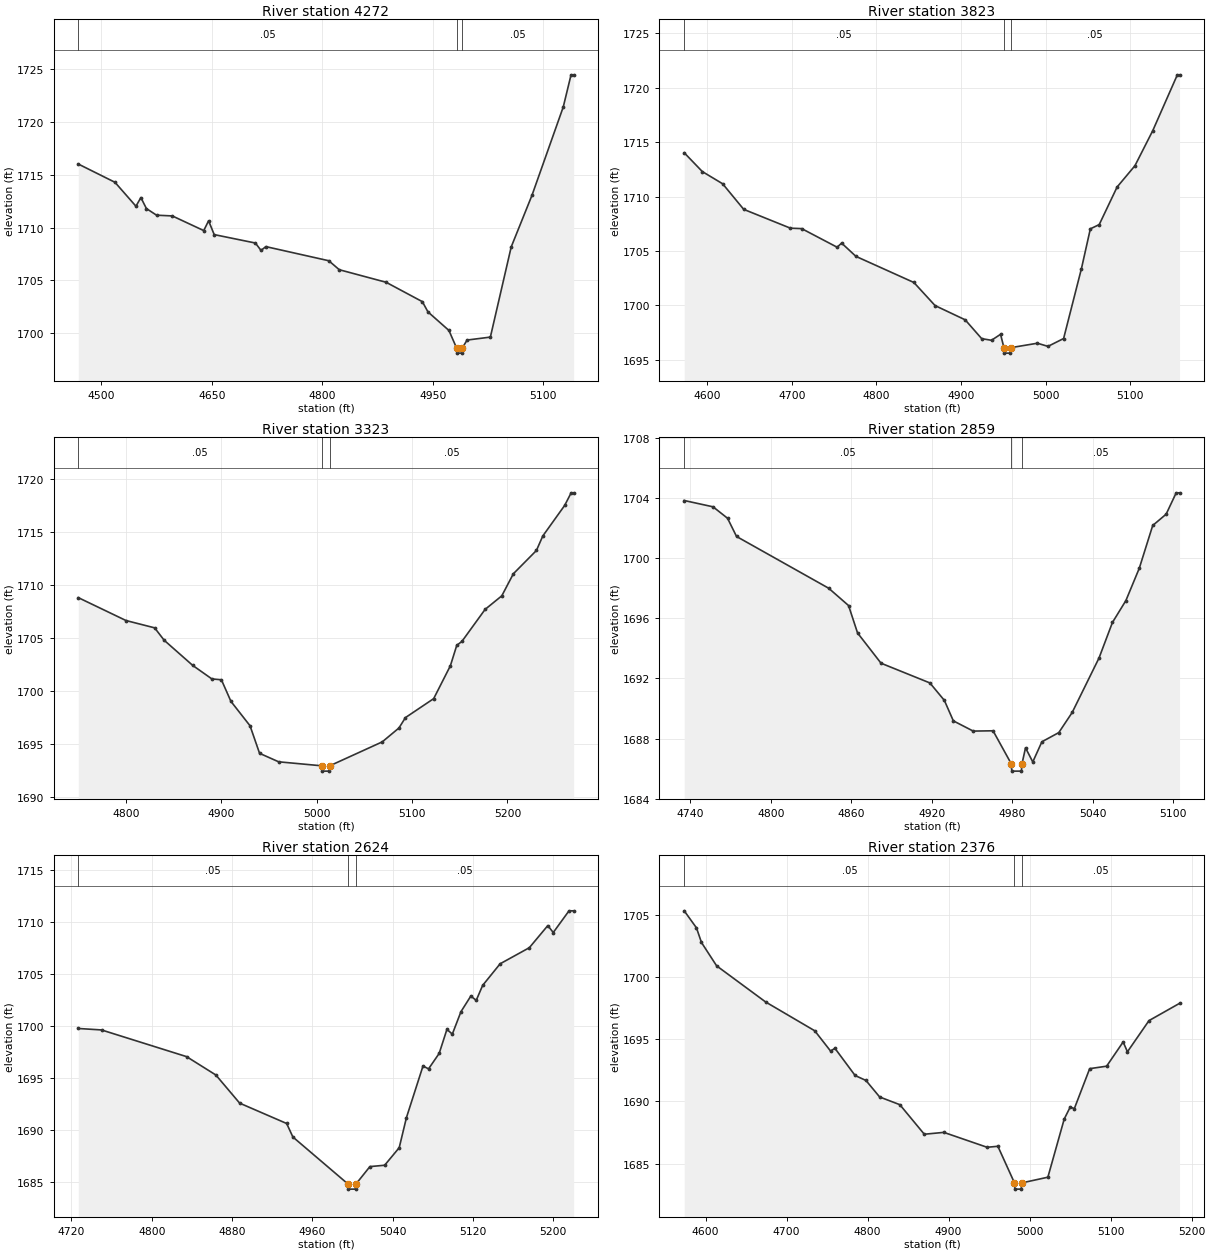
Type RM Length L Ch R = 1,4272,449,449,449
BEGIN DESCRIPTION:
Deadman 21 9.0
END DESCRIPTION:
XS GIS Cut Line= 3
      1644154.99      6922437.99      1644505.00      6922838.00
      1644604.97      6922937.97
#Sta/Elev= 30
  4468.6 1716.03  4518.4 1714.30  4546.9 1712.03  4553.6 1712.85  4561.1 1711.81
  4574.9 1711.18  4596.3 1711.11  4639.0 1709.72  4645.6 1710.65  4653.2 1709.34
  4709.2 1708.54  4716.8 1707.84  4723.4 1708.20  4808.9 1706.86  4823.1 1706.01
  4886.7 1704.82  4936.0 1702.98  4943.6 1702.01  4972.1 1700.25  4982.4 1698.60
  4982.9 1698.10  4989.8 1698.10  4990.3 1698.60  4996.8 1699.34  5028.4 1699.62
  5056.7 1708.17  5085.0 1713.08  5127.4 1721.44  5138.0 1724.49  5141.5 1724.49
#Mann=3,-1,0
  4468.6    0.05       0  4982.4    0.05       0  4990.3    0.05       0
Bank Sta=4982.4,4990.3
Exp/Cntr=0.3,0.1

Type RM Length L Ch R = 1,3823,500,500,500
BEGIN DESCRIPTION:
Deadman 21 8.0
END DESCRIPTION:
XS GIS Cut Line= 3
      1643955.00      6922588.01      1644105.00      6922988.00
      1644155.00      6923137.99
#Sta/Elev= 30
  4572.9 1714.03  4594.3 1712.30  4618.3 1711.18  4643.2 1708.83  4698.4 1707.10
  4711.7 1707.06  4753.6 1705.35  4758.9 1705.73  4775.8 1704.51  4844.3 1702.11
  4869.3 1699.99  4904.9 1698.68  4924.4 1696.95  4936.0 1696.80  4946.7 1697.35
  4950.7 1696.12  4951.2 1695.62  4958.2 1695.62  4958.7 1696.12  4990.3 1696.53
  5002.7 1696.24  5021.2 1696.96  5042.3 1703.39  5052.8 1707.04  5063.3 1707.43
  5084.4 1710.88  5105.5 1712.84  5126.6 1716.07  5155.6 1721.19  5158.2 1721.19
#Mann=3,-1,0
  4572.9    0.05       0  4950.7    0.05       0  4958.7    0.05       0
Bank Sta=4950.7,4958.7
Exp/Cntr=0.3,0.1

Type RM Length L Ch R = 1,3323,464,464,464
BEGIN DESCRIPTION:
Deadman 21 7.0
END DESCRIPTION:
XS GIS Cut Line= 3
      1643605.00      6922738.01      1643605.00      6922988.00
      1643704.98      6923237.96
#Sta/Elev= 30
  4750.2 1708.79  4800.2 1706.63  4830.2 1705.94  4840.2 1704.77  4870.2 1702.39
  4890.2 1701.12  4900.2 1701.04  4910.2 1699.00  4930.2 1696.70  4940.2 1694.10
  4960.2 1693.30  5005.6 1692.92  5006.1 1692.42  5013.2 1692.42  5013.7 1692.92
  5068.8 1695.18  5086.3 1696.49  5093.1 1697.47  5122.7 1699.26  5140.2 1702.36
  5146.9 1704.29  5152.3 1704.66  5176.6 1707.68  5194.1 1708.96  5206.2 1711.04
  5230.4 1713.24  5237.1 1714.61  5260.0 1717.49  5266.8 1718.68  5269.4 1718.68
#Mann=3,-1,0
  4750.2    0.05       0  5005.6    0.05       0  5013.7    0.05       0
Bank Sta=5005.6,5013.7
Exp/Cntr=0.3,0.1

Type RM Length L Ch R = 1,2859,235,235,235
BEGIN DESCRIPTION:
Deadman 21 6.0
END DESCRIPTION:
XS GIS Cut Line= 3
      1643255.00      6922788.01      1643155.00      6923038.00
      1643155.00      6923137.95
#Sta/Elev= 30
  4735.4 1703.82  4756.9 1703.40  4767.7 1702.64  4774.4 1701.43  4843.1 1697.99
  4857.9 1696.84  4864.6 1695.02  4882.1 1693.01  4918.5 1691.70  4929.3 1690.54
  4936.0 1689.18  4950.8 1688.50  4965.6 1688.52  4979.1 1686.34  4979.6 1685.84
  4986.7 1685.84  4987.2 1686.34  4989.8 1687.39  4995.2 1686.45  5002.0 1687.79
  5014.6 1688.40  5024.6 1689.74  5044.6 1693.36  5054.6 1695.72  5064.6 1697.17
  5074.6 1699.32  5084.6 1702.16  5094.6 1702.91  5102.1 1704.33  5104.6 1704.33
#Mann=3,-1,0
  4735.4    0.05       0  4979.1    0.05       0  4987.2    0.05       0
Bank Sta=4979.1,4987.2
Exp/Cntr=0.3,0.1

Type RM Length L Ch R = 1,2624,248,248,248
BEGIN DESCRIPTION:
Mapping XS 5fc11f9d
END DESCRIPTION:
XS GIS Cut Line= 2
      1643043.01      6922736.66      1642852.05      6923191.50
#Sta/Elev= 30
  4726.9 1699.77  4750.0 1699.63  4834.7 1697.06  4863.9 1695.29  4887.6 1692.58
  4934.4 1690.62  4940.6 1689.32  4995.4 1684.80  4995.9 1684.30  5003.0 1684.30
  5003.5 1684.80  5017.3 1686.47  5032.0 1686.60  5046.5 1688.29  5053.7 1691.19
  5070.2 1696.16  5075.7 1695.88  5086.3 1697.37  5094.0 1699.68  5099.4 1699.23
  5108.0 1701.39  5117.8 1702.89  5123.2 1702.48  5129.6 1703.92  5147.0 1706.00
  5176.1 1707.55  5194.5 1709.68  5199.9 1709.01  5215.6 1711.10  5220.2 1711.10
#Mann=3,-1,0
  4726.9    0.05       0  4995.4    0.05       0  5003.5    0.05       0
Bank Sta=4995.4,5003.5
Exp/Cntr=0.3,0.1

Type RM Length L Ch R = 1,2376,481,481,481
BEGIN DESCRIPTION:
Deadman 21 5.0
END DESCRIPTION:
XS GIS Cut Line= 3
      1642555.01      6922538.02      1642705.00      6922938.00
      1642650.99      6923114.03
#Sta/Elev= 30
  4573.7 1705.35  4588.8 1703.98  4595.0 1702.80  4613.7 1700.92  4674.2 1698.01
  4734.8 1695.69  4754.3 1694.06  4759.7 1694.28  4784.6 1692.09  4798.0 1691.69
  4814.9 1690.36  4839.8 1689.74  4870.0 1687.36  4894.1 1687.51  4947.5 1686.31
  4960.8 1686.39  4981.3 1683.44  4981.8 1682.94  4989.7 1682.94  4990.2 1683.44
  5022.5 1683.90  5042.7 1688.59  5050.0 1689.54  5055.2 1689.43  5074.1 1692.64
  5095.0 1692.84  5115.4 1694.79  5120.7 1694.00  5147.3 1696.51  5185.0 1697.90
#Mann=3,-1,0
  4573.7    0.05       0  4981.3    0.05       0  4990.2    0.05       0
Bank Sta=4981.3,4990.2
Exp/Cntr=0.3,0.1

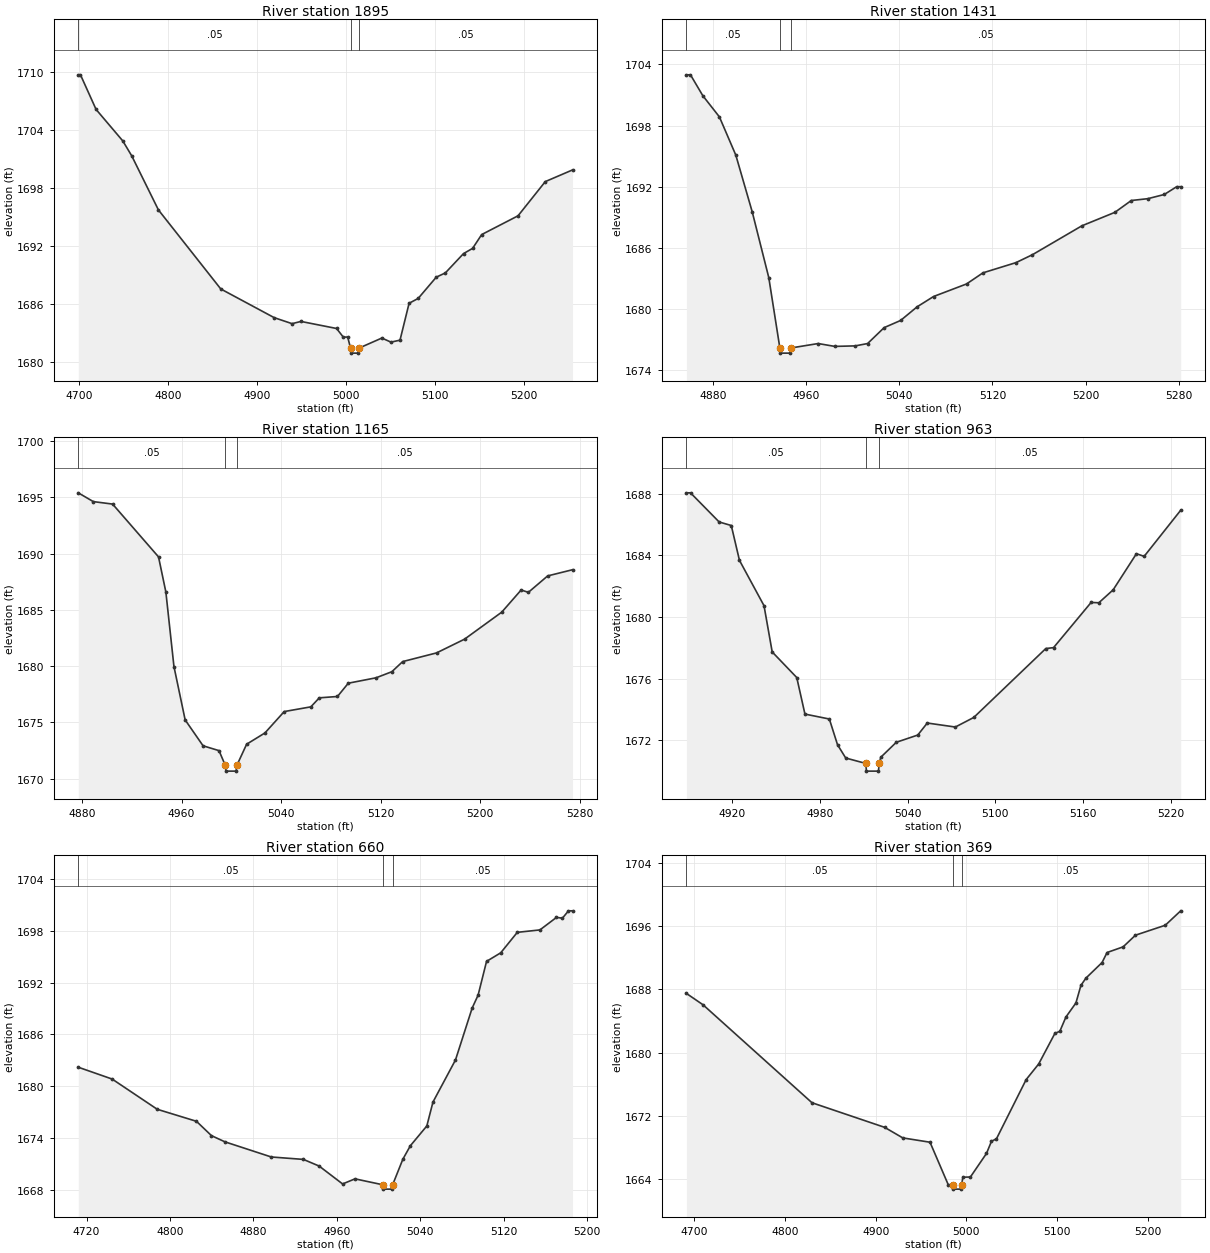
Type RM Length L Ch R = 1,1895,464,464,464
BEGIN DESCRIPTION:
Deadman 21 4.0
END DESCRIPTION:
XS GIS Cut Line= 3
      1642255.00      6922538.03      1642255.00      6922838.00
      1642305.00      6923087.98
#Sta/Elev= 30
  4699.5 1709.72  4702.0 1709.72  4719.5 1706.14  4749.5 1702.88  4759.5 1701.34
  4789.5 1695.74  4859.5 1687.56  4919.5 1684.59  4939.5 1683.97  4949.5 1684.20
  4989.5 1683.47  4997.0 1682.58  5002.0 1682.58  5005.2 1681.42  5005.7 1680.92
  5013.7 1680.92  5014.2 1681.42  5040.3 1682.48  5050.5 1682.06  5060.7 1682.26
  5070.9 1686.08  5081.1 1686.58  5101.4 1688.78  5111.6 1689.22  5132.0 1691.22
  5142.2 1691.76  5152.4 1693.19  5193.2 1695.13  5223.8 1698.67  5254.4 1699.88
#Mann=3,-1,0
  4699.5    0.05       0  5005.2    0.03       0  5014.2    0.05       0
Bank Sta=5005.2,5014.2
Exp/Cntr=0.3,0.1

Type RM Length L Ch R = 1,1431,266,266,266
BEGIN DESCRIPTION:
Deadman 21 3.0
END DESCRIPTION:
XS GIS Cut Line= 3
      1641705.02      6922788.02      1641805.00      6922888.00
      1642004.97      6923087.97
#Sta/Elev= 30
  4857.4 1702.97  4860.9 1702.97  4871.5 1700.92  4885.7 1698.85  4899.8 1695.10
  4913.9 1689.53  4928.1 1683.09  4937.6 1676.19  4938.1 1675.69  4946.3 1675.69
  4946.8 1676.19  4970.5 1676.63  4984.7 1676.35  5002.3 1676.40  5012.9 1676.63
  5027.1 1678.19  5041.2 1678.89  5055.4 1680.23  5069.5 1681.24  5097.8 1682.47
  5111.9 1683.56  5140.2 1684.56  5154.4 1685.34  5196.8 1688.17  5225.1 1689.49
  5239.2 1690.65  5253.4 1690.83  5267.5 1691.24  5278.1 1692.00  5281.6 1692.00
#Mann=3,-1,0
  4857.4    0.05       0  4937.6    0.03       0  4946.8    0.05       0
Bank Sta=4937.6,4946.8
Exp/Cntr=0.3,0.1

Type RM Length L Ch R = 1,1165,202,202,202
BEGIN DESCRIPTION:
Mapping XS f7ae0ee4
END DESCRIPTION:
XS GIS Cut Line= 2
      1641529.09      6922997.07      1641869.38      6923201.94
#Sta/Elev= 30
  4877.0 1695.39  4889.1 1694.61  4904.6 1694.39  4941.5 1689.70  4947.4 1686.58
  4953.9 1679.96  4962.9 1675.22  4977.3 1672.92  4990.1 1672.49  4995.2 1671.17
  4995.7 1670.67  5003.9 1670.67  5004.4 1671.17  5012.3 1673.06  5027.0 1674.06
  5042.5 1675.96  5063.9 1676.38  5070.7 1677.18  5085.3 1677.30  5094.0 1678.48
  5116.3 1678.96  5129.0 1679.50  5137.7 1680.40  5164.9 1681.17  5187.4 1682.39
  5217.3 1684.79  5232.9 1686.76  5238.7 1686.55  5254.2 1688.01  5274.2 1688.56
#Mann=3,-1,0
  4877.0    0.05       0  4995.2    0.05       0  5004.4    0.05       0
Bank Sta=4995.2,5004.4
Exp/Cntr=0.3,0.1

Type RM Length L Ch R = 1,963,303,303,303
BEGIN DESCRIPTION:
Deadman 21 2.0
END DESCRIPTION:
XS GIS Cut Line= 3
      1641505.00      6923138.00      1641555.00      6923238.00
      1641768.60      6923313.02
#Sta/Elev= 30
  4888.7 1688.06  4891.5 1688.06  4911.1 1686.17  4919.4 1685.94  4925.0 1683.68
  4941.8 1680.74  4947.4 1677.74  4964.2 1676.08  4969.8 1673.71  4986.5 1673.39
  4992.1 1671.72  4997.7 1670.86  5011.4 1670.51  5011.9 1670.01  5020.1 1670.01
  5020.6 1670.51  5021.7 1670.91  5032.3 1671.88  5047.0 1672.35  5053.5 1673.13
  5072.7 1672.87  5085.3 1673.49  5134.6 1677.96  5139.9 1678.02  5165.6 1680.95
  5170.9 1680.93  5180.7 1681.77  5196.6 1684.11  5201.9 1683.94  5226.9 1686.93
#Mann=3,-1,0
  4888.7    0.05       0  5011.4    0.05       0  5020.6    0.05       0
Bank Sta=5011.4,5020.6
Exp/Cntr=0.3,0.1

Type RM Length L Ch R = 1,660,291,291,291
BEGIN DESCRIPTION:
Mapping XS a026d21b
END DESCRIPTION:
XS GIS Cut Line= 2
      1641292.99      6923236.64      1641525.63      6923649.85
#Sta/Elev= 30
  4712.0 1682.21  4744.5 1680.84  4787.8 1677.34  4825.4 1675.95  4839.8 1674.29
  4852.8 1673.57  4897.2 1671.82  4928.0 1671.54  4943.1 1670.77  4965.6 1668.70
  4977.5 1669.29  5004.3 1668.60  5004.8 1668.10  5013.1 1668.10  5013.6 1668.60
  5023.4 1671.56  5030.6 1673.12  5046.4 1675.41  5052.3 1678.18  5073.9 1683.05
  5089.9 1689.06  5095.6 1690.55  5103.7 1694.46  5117.3 1695.45  5133.2 1697.82
  5154.9 1698.10  5170.8 1699.55  5176.5 1699.46  5182.3 1700.31  5186.2 1700.31
#Mann=3,-1,0
  4712.0    0.05       0  5004.3    0.05       0  5013.6    0.05       0
Bank Sta=5004.3,5013.6
Exp/Cntr=0.3,0.1

Type RM Length L Ch R = 1,369,293,293,293
BEGIN DESCRIPTION:
Mapping XS 20b2566e
END DESCRIPTION:
XS GIS Cut Line= 3
      1641161.06      6923229.70      1641157.59      6923535.28
      1641254.57      6923753.50
#Sta/Elev= 30
  4691.6 1687.50  4709.9 1686.06  4829.9 1673.63  4909.9 1670.51  4929.9 1669.17
  4959.9 1668.62  4979.9 1663.25  4985.2 1663.17  4985.7 1662.67  4994.1 1662.67
  4994.6 1663.17  4996.1 1664.18  5004.4 1664.21  5022.1 1667.20  5027.6 1668.74
  5033.1 1669.06  5065.8 1676.57  5079.6 1678.55  5097.4 1682.42  5102.9 1682.70
  5109.6 1684.51  5120.6 1686.29  5126.1 1688.52  5131.6 1689.44  5149.4 1691.42
  5154.9 1692.69  5172.6 1693.41  5186.2 1694.89  5219.0 1696.15  5236.0 1697.98
#Mann=3,-1,0
  4691.6    0.05       0  4985.2    0.05       0  4994.6    0.05       0
Bank Sta=4985.2,4994.6
Exp/Cntr=0.3,0.1

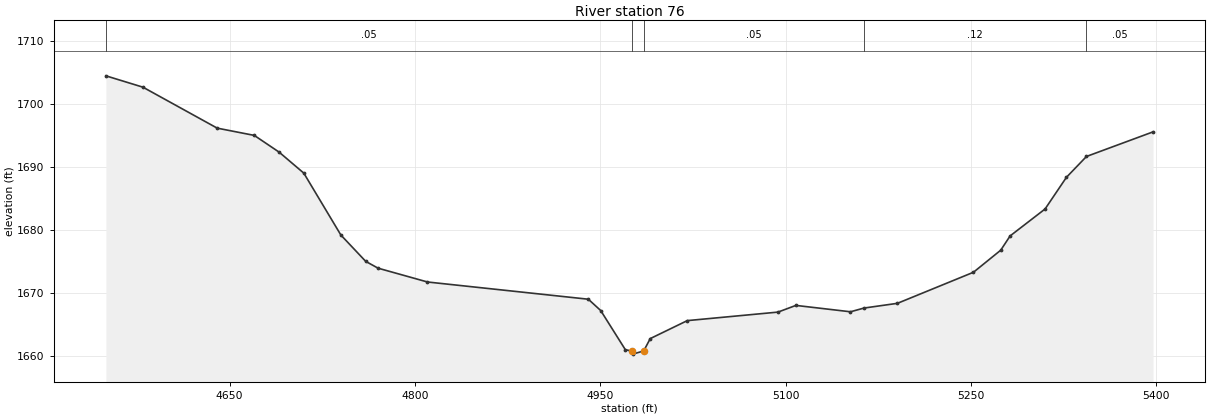
Type RM Length L Ch R = 1,76,0,0,0
BEGIN DESCRIPTION:
Deadman 21 1.0
END DESCRIPTION:
XS GIS Cut Line= 3
      1640905.00      6923138.03      1640880.00      6923613.00
      1641216.58      6923771.37
#Sta/Elev= 30
  4549.9 1704.44  4579.9 1702.64  4640.0 1696.15  4670.0 1695.00  4690.1 1692.35
  4710.1 1689.02  4740.1 1679.21  4760.2 1675.04  4770.2 1673.96  4810.2 1671.77
  4940.4 1669.04  4950.4 1667.25  4970.4 1661.03  4975.7 1660.84  4976.2 1660.34
  4985.2 1660.84  4990.5 1662.80  5020.5 1665.65  5093.9 1667.00  5108.4 1668.06
  5152.6 1667.05  5163.5 1667.64  5190.6 1668.39  5252.1 1673.31  5274.2 1676.81
  5281.8 1679.07  5310.1 1683.34  5327.4 1688.36  5343.6 1691.66  5397.5 1695.56
#Mann=5,-1,0
  4549.9    0.05       0  4975.7    0.03       0  4985.2    0.05       0
  5163.5    0.12       0  5343.6    0.05       0
Bank Sta=4975.7,4985.2
Exp/Cntr=0.3,0.1

Chan Stop Cuts=-1