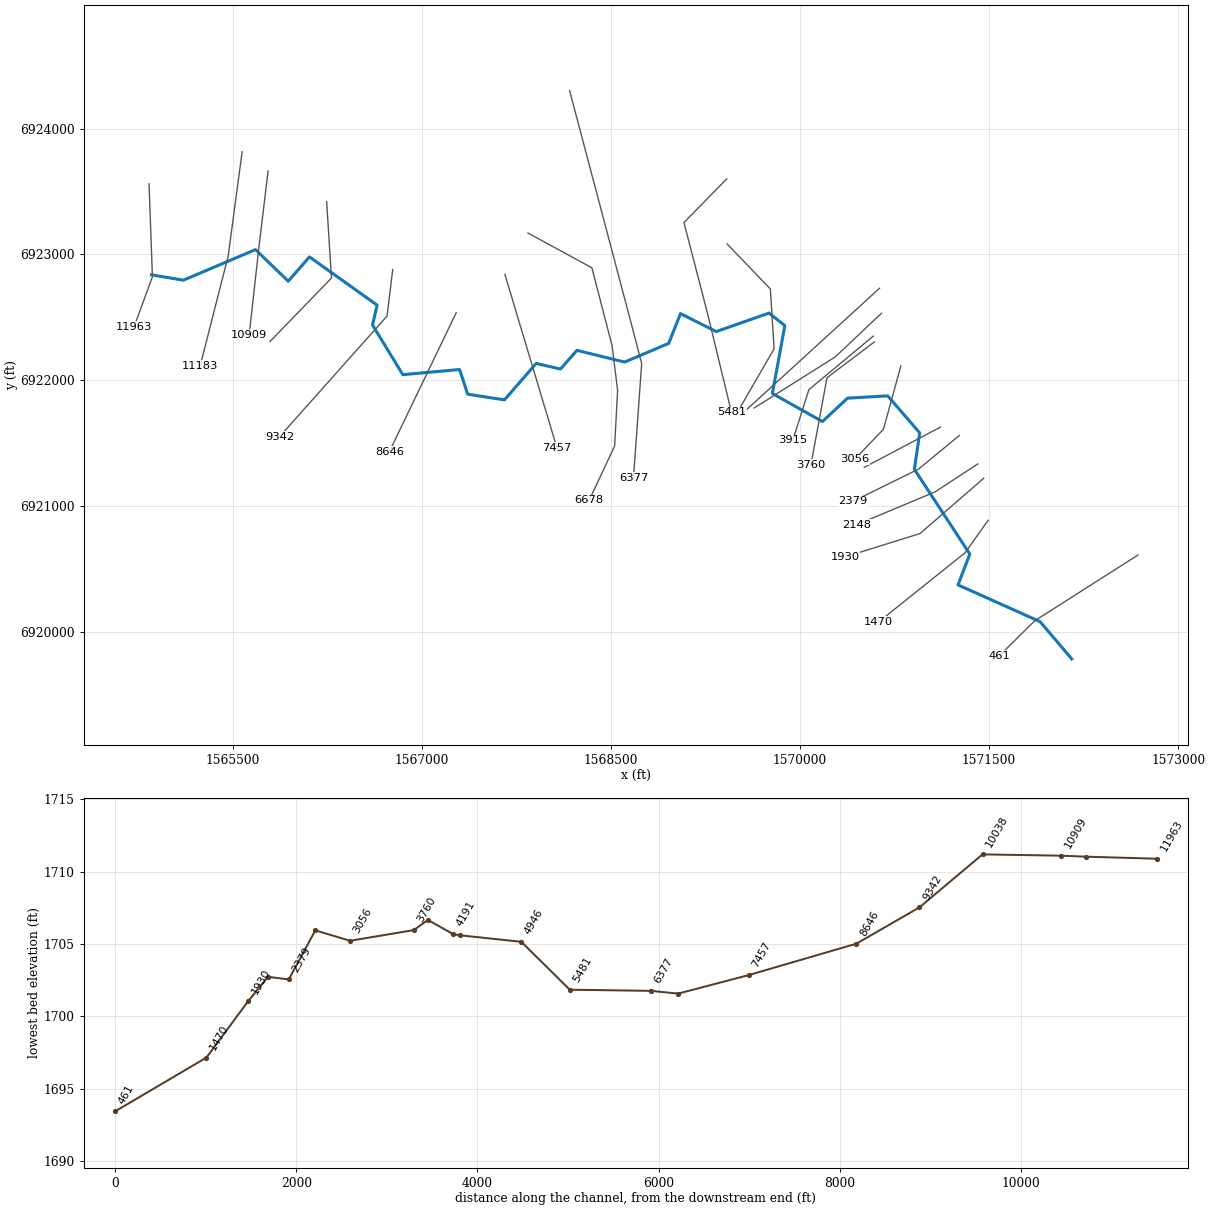
--- Deadman 22.prj (project) ---

Proj Title=Deadman 22 Base Level Engineering
Current Plan=p01
Default Exp/Contr=0.3,0.1
English Units
Geom File=g01
Flow File=f01
Plan File=p01
BEGIN DESCRIPTION:
Deadman 22
END DESCRIPTION:

--- Deadman 22.p01 (plan) ---

Plan Title=Multiple Run
Short Identifier=Multiple
Geom File=g01
Flow File=f01
Subcritical Flow
K Sum by GR= 0
Std Step Tol= 0.01
Critical Tol= 0.01
Num of Std Step Trials= 20
Max Error Tol= 0.3
Flow Tol Ratio= 0.001
Split Flow NTrial= 30
Split Flow Tol= 0.02
Split Flow Ratio= 0.02
Log Output Level= 0
Friction Slope Method= 1
Unsteady Friction Slope Method= 2
Unsteady Bridges Friction Slope Method= 1
Parabolic Critical Depth
Global Vel Dist=  1 , 1 , 1
Global Log Level= 0
CheckData=True
Encroach Param= -1, 0, 0, 0
BEGIN DESCRIPTION:
Multiple Run
END DESCRIPTION:

--- Deadman 22.f01 (steady flow) ---

Flow Title=Multiple
Number of Profiles=7
Profile Names=10-year,25-year,50-year,1pct_min,100-year,1pct_plu,500-year
River Rch & RM= Deadman 22,Reach-1,11963
      67      81      91      51     101     202     127
River Rch & RM= Deadman 22,Reach-1,11183
     146     188     220     127     254     507     345
River Rch & RM= Deadman 22,Reach-1,461
     170     220     259     151     301     600     413
Boundary for River Rch & Prof#=Deadman 22,Reach-1,1
Up Type=0
Dn Type=3
Dn Slope=0.005
Boundary for River Rch & Prof#=Deadman 22,Reach-1,2
Up Type=0
Dn Type=3
Dn Slope=0.005
Boundary for River Rch & Prof#=Deadman 22,Reach-1,3
Up Type=0
Dn Type=3
Dn Slope=0.005
Boundary for River Rch & Prof#=Deadman 22,Reach-1,4
Up Type=0
Dn Type=3
Dn Slope=0.005
Boundary for River Rch & Prof#=Deadman 22,Reach-1,5
Up Type=0
Dn Type=3
Dn Slope=0.005
Boundary for River Rch & Prof#=Deadman 22,Reach-1,6
Up Type=0
Dn Type=3
Dn Slope=0.005
Boundary for River Rch & Prof#=Deadman 22,Reach-1,7
Up Type=0
Dn Type=3
Dn Slope=0.005

--- Deadman 22.g01 (geometry) ---

Geom Title=Existing Conditions

River Reach=Deadman 22,Reach-1
Reach XY= 30
      1564855.00      6922838.00      1565108.40      6922795.84
      1565680.12      6923038.52      1565939.76      6922787.84
      1566108.32      6922980.42      1566644.82      6922597.71
      1566608.34      6922439.72      1566848.67      6922045.34
      1567299.16      6922086.43      1567363.10      6921890.47
      1567655.02      6921845.08      1567906.63      6922134.87
      1568099.29      6922089.89      1568229.88      6922238.53
      1568608.58      6922145.50      1568957.57      6922293.69
      1569051.38      6922530.14      1569334.79      6922387.64
      1569753.36      6922534.40      1569879.04      6922434.60
      1569780.15      6921895.87      1570177.19      6921673.00
      1570376.44      6921858.97      1570695.01      6921877.05
      1570949.12      6921582.97      1570906.62      6921294.03
      1571346.15      6920620.64      1571253.16      6920375.63
      1571903.57      6920084.11      1572155.00      6919788.00

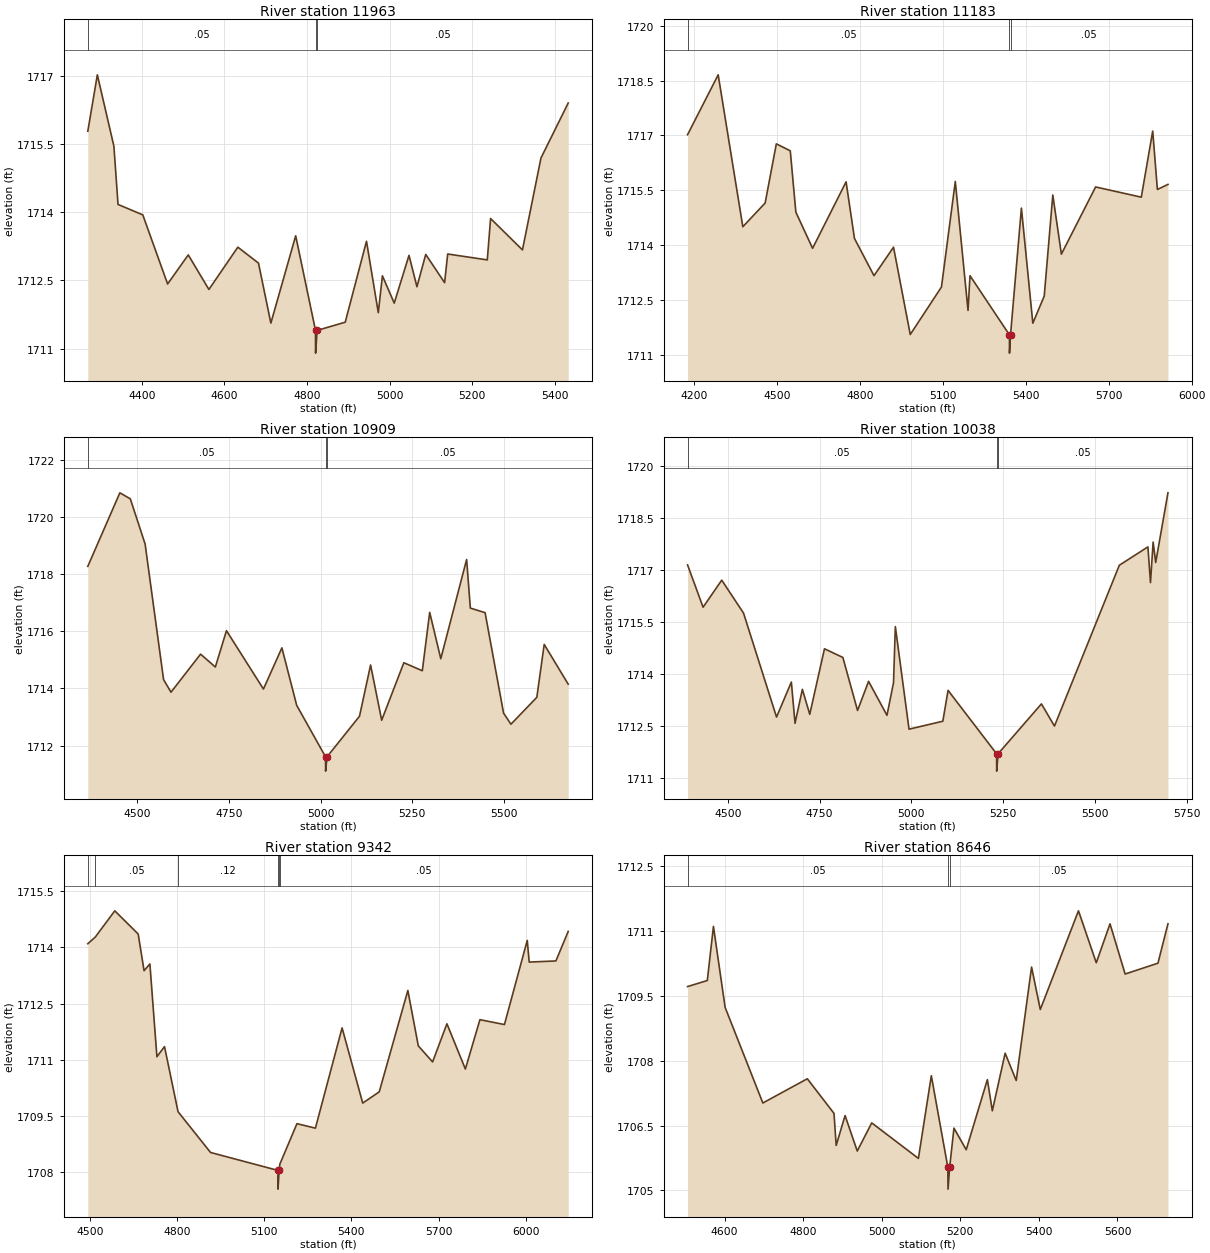
Type RM Length L Ch R = 1,11963,780,780,780
BEGIN DESCRIPTION:
Deadman 22 9.0
END DESCRIPTION:
XS GIS Cut Line= 3
      1564835.59      6923561.13      1564862.44      6922822.98
      1564716.22      6922423.96
#Sta/Elev= 30
  4269.2 1715.78  4292.3 1717.02  4332.4 1715.45  4342.4 1714.17  4402.4 1713.94
  4462.5 1712.42  4512.5 1713.06  4562.5 1712.30  4632.6 1713.23  4682.6 1712.88
  4712.6 1711.56  4772.7 1713.48  4820.7 1711.40  4820.9 1710.90  4824.7 1711.40
  4892.7 1711.58  4944.2 1713.36  4972.8 1711.79  4982.8 1712.60  5011.4 1712.00
  5047.2 1713.05  5066.4 1712.36  5087.7 1713.07  5133.4 1712.45  5140.9 1713.08
  5236.8 1712.95  5244.8 1713.86  5322.0 1713.17  5366.8 1715.19  5432.8 1716.40
#Mann=3,-1,0
  4269.2    0.05       0  4820.7    0.05       0  4824.7    0.05       0
Bank Sta=4820.7,4824.7
Exp/Cntr=0.3,0.1

Type RM Length L Ch R = 1,11183,274,274,274
BEGIN DESCRIPTION:
Deadman 22 8.0
END DESCRIPTION:
XS GIS Cut Line= 3
      1565574.25      6923816.01      1565463.14      6922986.17
      1565240.91      6922114.61
#Sta/Elev= 30
  4177.6 1717.02  4288.3 1718.66  4377.4 1714.50  4458.1 1715.15  4498.5 1716.77
  4548.9 1716.58  4569.1 1714.90  4629.6 1713.91  4750.7 1715.73  4781.0 1714.18
  4851.6 1713.16  4922.2 1713.94  4982.7 1711.55  5095.5 1712.85  5145.5 1715.74
  5191.5 1712.21  5198.7 1713.16  5341.2 1711.54  5341.4 1711.04  5345.2 1711.54
  5384.5 1715.01  5425.8 1711.86  5467.0 1712.60  5498.0 1715.37  5529.0 1713.75
  5652.8 1715.59  5817.9 1715.31  5859.2 1717.12  5876.1 1715.52  5914.3 1715.66
#Mann=3,-1,0
  4177.6    0.05       0  5341.2    0.05       0  5345.2    0.05       0
Bank Sta=5341.2,5345.2
Exp/Cntr=0.3,0.1

Type RM Length L Ch R = 1,10909,871,871,871
BEGIN DESCRIPTION:
Deadman 22 7.0
END DESCRIPTION:
XS GIS Cut Line= 3
      1565780.00      6923662.96      1565705.00      6923038.00
      1565630.00      6922363.00
#Sta/Elev= 30
  4365.9 1718.27  4453.2 1720.84  4481.7 1720.63  4522.0 1719.05  4572.3 1714.31
  4592.5 1713.87  4673.1 1715.20  4713.3 1714.75  4743.6 1716.02  4844.3 1713.98
  4894.6 1715.42  4934.9 1713.41  5013.5 1711.61  5013.7 1711.11  5017.5 1711.61
  5106.0 1713.03  5136.2 1714.82  5166.4 1712.89  5226.8 1714.90  5277.1 1714.62
  5297.2 1716.66  5327.4 1715.04  5397.8 1718.51  5407.9 1716.81  5448.1 1716.65
  5498.4 1713.14  5518.5 1712.75  5589.0 1713.69  5609.1 1715.54  5674.5 1714.15
#Mann=3,-1,0
  4365.9    0.05       0  5013.5    0.03       0  5017.5    0.05       0
Bank Sta=5013.5,5017.5
Exp/Cntr=0.3,0.1

Type RM Length L Ch R = 1,10038,696,696,696
BEGIN DESCRIPTION:
Mapping XS c6341497
END DESCRIPTION:
XS GIS Cut Line= 3
      1566244.39      6923420.21      1566282.85      6922812.44
      1565795.89      6922309.84
#Sta/Elev= 30
  4390.1 1717.15  4432.4 1715.93  4483.2 1716.71  4542.6 1715.76  4632.5 1712.76
  4672.9 1713.77  4682.9 1712.58  4702.9 1713.56  4723.0 1712.84  4763.1 1714.73
  4813.2 1714.48  4853.2 1712.95  4883.3 1713.79  4933.4 1712.81  4951.2 1713.75
  4956.2 1715.37  4993.5 1712.41  5085.6 1712.64  5099.8 1713.53  5232.1 1711.70
  5232.3 1711.20  5236.1 1711.70  5354.2 1713.14  5389.7 1712.50  5566.4 1717.14
  5644.3 1717.67  5651.3 1716.64  5658.5 1717.81  5665.5 1717.22  5698.9 1719.23
#Mann=3,-1,0
  4390.1    0.05       0  5232.1    0.05       0  5236.1    0.05       0
Bank Sta=5232.1,5236.1
Exp/Cntr=0.3,0.1

Type RM Length L Ch R = 1,9342,696,696,696
BEGIN DESCRIPTION:
Deadman 22 6.0
END DESCRIPTION:
XS GIS Cut Line= 3
      1566768.74      6922880.35      1566723.56      6922510.48
      1565870.63      6921552.60
#Sta/Elev= 30
  4491.7 1714.10  4517.6 1714.28  4584.7 1714.98  4665.3 1714.36  4685.5 1713.38
  4705.6 1713.56  4729.8 1711.08  4756.0 1711.35  4802.6 1709.61  4914.6 1708.52
  5146.8 1708.04  5147.0 1707.54  5150.8 1708.04  5153.5 1708.21  5212.3 1709.29
  5275.9 1709.17  5367.8 1711.85  5438.9 1709.84  5495.8 1710.14  5594.4 1712.85
  5630.4 1711.37  5679.7 1710.94  5729.0 1711.96  5792.6 1710.75  5842.7 1712.07
  5927.2 1711.94  6005.8 1714.19  6012.5 1713.61  6104.5 1713.64  6146.9 1714.43
#Mann=6,-1,0
  4491.7    0.12       0  4517.6    0.05       0  4802.6    0.12       0
  5146.8    0.07       0  5150.8    0.12       0  5153.5    0.05       0
Bank Sta=5146.8,5150.8
Exp/Cntr=0.3,0.1

Type RM Length L Ch R = 1,8646,1189,1189,1189
BEGIN DESCRIPTION:
Mapping XS fadc0f4b
END DESCRIPTION:
XS GIS Cut Line= 2
      1567272.19      6922537.43      1566742.68      6921435.00
#Sta/Elev= 30
  4505.6 1709.71  4555.9 1709.85  4571.5 1711.10  4601.2 1709.23  4697.3 1707.02
  4810.5 1707.58  4878.4 1706.78  4884.0 1706.04  4906.6 1706.73  4937.6 1705.91
  4974.5 1706.56  5093.3 1705.74  5126.2 1707.65  5168.3 1705.53  5168.7 1705.03
  5172.8 1705.53  5183.8 1706.44  5215.0 1705.94  5268.9 1707.56  5281.5 1706.84
  5314.1 1708.17  5342.3 1707.54  5381.4 1710.16  5403.6 1709.18  5500.8 1711.46
  5546.1 1710.26  5581.1 1711.16  5619.6 1710.00  5703.1 1710.25  5728.6 1711.16
#Mann=3,-1,0
  4505.6    0.05       0  5168.3    0.03       0  5172.8    0.05       0
Bank Sta=5168.3,5172.8
Exp/Cntr=0.3,0.1

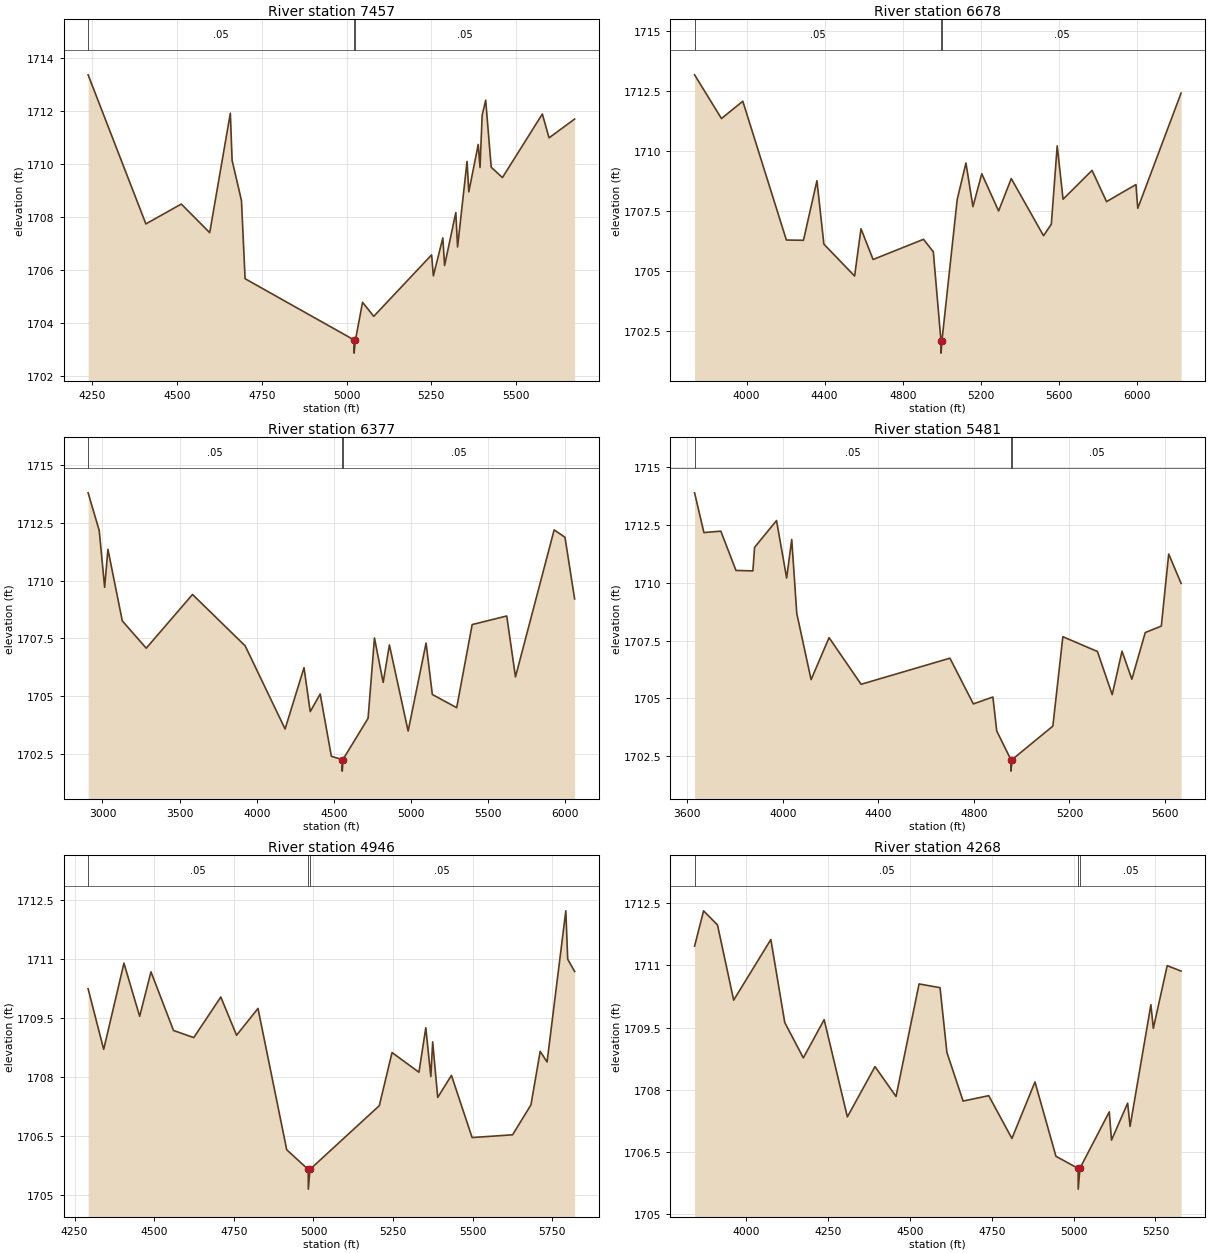
Type RM Length L Ch R = 1,7457,779,779,779
BEGIN DESCRIPTION:
Mapping XS e3ce0a97
END DESCRIPTION:
XS GIS Cut Line= 2
      1567658.50      6922841.27      1568070.42      6921466.76
#Sta/Elev= 30
  4237.6 1713.37  4408.0 1707.74  4512.4 1708.49  4596.2 1707.41  4657.1 1711.92
  4662.3 1710.14  4689.9 1708.62  4700.6 1705.67  5021.7 1703.36  5022.0 1702.86
  5026.2 1703.36  5047.0 1704.78  5080.1 1704.25  5250.7 1706.57  5255.9 1705.78
  5283.8 1707.21  5289.0 1706.17  5322.1 1708.17  5327.3 1706.87  5355.2 1710.10
  5360.4 1708.95  5388.2 1710.74  5393.5 1709.87  5399.8 1711.85  5410.2 1712.41
  5426.5 1709.88  5459.6 1709.49  5577.3 1711.89  5597.1 1710.99  5672.5 1711.70
#Mann=3,-1,0
  4237.6    0.05       0  5021.7    0.05       0  5026.2    0.05       0
Bank Sta=5021.7,5026.2
Exp/Cntr=0.3,0.1

Type RM Length L Ch R = 1,6678,301,301,301
BEGIN DESCRIPTION:
Mapping XS 58509ec3
END DESCRIPTION:
XS GIS Cut Line= 6
      1567841.42      6923170.09      1568348.54      6922894.13
      1568509.19      6922272.71      1568552.59      6921921.15
      1568528.95      6921479.10      1568327.57      6921048.57
#Sta/Elev= 30
  3733.8 1713.17  3871.5 1711.35  3980.7 1712.07  4203.9 1706.29  4291.3 1706.28
  4360.4 1708.76  4395.9 1706.12  4553.3 1704.79  4586.0 1706.76  4648.0 1705.48
  4906.2 1706.32  4956.3 1705.80  4995.7 1702.08  4996.0 1701.58  5000.3 1702.08
  5078.6 1707.97  5123.4 1709.50  5159.3 1707.68  5204.5 1709.05  5290.7 1707.50
  5355.6 1708.85  5520.7 1706.47  5560.7 1706.95  5590.8 1710.21  5620.8 1707.99
  5769.3 1709.19  5843.4 1707.89  5994.0 1708.60  6003.3 1707.61  6225.2 1712.41
#Mann=3,-1,0
  3733.8    0.05       0  4995.7    0.03       0  5000.3    0.05       0
Bank Sta=4995.7,5000.3
Exp/Cntr=0.3,0.1

Type RM Length L Ch R = 1,6377,896,896,896
BEGIN DESCRIPTION:
Mapping XS 4367944f
END DESCRIPTION:
XS GIS Cut Line= 4
      1568171.47      6924302.17      1568665.44      6922433.30
      1568743.56      6922133.82      1568678.41      6921225.71
#Sta/Elev= 30
  2907.1 1713.79  2979.1 1712.16  3014.2 1709.71  3035.5 1711.35  3128.6 1708.26
  3283.8 1707.08  3583.7 1709.40  3925.1 1707.18  4183.7 1703.59  4306.4 1706.24
  4346.6 1704.34  4411.2 1705.10  4483.6 1702.41  4553.7 1702.27  4554.0 1701.77
  4558.3 1702.27  4721.5 1704.05  4762.9 1707.52  4819.3 1705.60  4859.7 1707.22
  4981.1 1703.50  5097.4 1707.30  5137.9 1705.08  5295.8 1704.51  5396.1 1708.10
  5620.2 1708.47  5676.8 1705.84  5927.5 1712.19  5997.6 1711.87  6060.1 1709.21
#Mann=3,-1,0
  2907.1    0.05       0  4553.7    0.03       0  4558.3    0.05       0
Bank Sta=4553.7,4558.3
Exp/Cntr=0.3,0.1

Type RM Length L Ch R = 1,5481,535,535,535
BEGIN DESCRIPTION:
Mapping XS ae8623eb
END DESCRIPTION:
XS GIS Cut Line= 4
      1569418.24      6923600.11      1569078.72      6923253.63
      1569264.40      6922537.46      1569455.36      6921747.56
#Sta/Elev= 30
  3630.0 1713.90  3669.1 1712.18  3739.9 1712.24  3803.4 1710.54  3874.2 1710.52
  3881.3 1711.54  3973.2 1712.70  4015.6 1710.21  4036.9 1711.88  4058.0 1708.68
  4118.0 1705.81  4193.2 1707.63  4327.5 1705.61  4699.4 1706.74  4797.6 1704.76
  4879.4 1705.06  4895.5 1703.59  4954.6 1702.35  4955.1 1701.85  4959.9 1702.35
  5130.6 1703.80  5172.4 1707.67  5317.3 1707.03  5379.1 1705.16  5420.2 1707.04
  5461.4 1705.83  5517.5 1707.85  5584.8 1708.13  5615.7 1711.25  5667.6 1709.98
#Mann=3,-1,0
  3630.0    0.05       0  4954.6    0.05       0  4959.9    0.05       0
Bank Sta=4954.6,4959.9
Exp/Cntr=0.3,0.1

Type RM Length L Ch R = 1,4946,678,678,678
BEGIN DESCRIPTION:
Mapping XS 2e3eff9a
END DESCRIPTION:
XS GIS Cut Line= 4
      1569421.30      6923083.28      1569764.43      6922725.59
      1569793.91      6922251.01      1569516.12      6921769.21
#Sta/Elev= 30
  4292.5 1710.25  4341.4 1708.71  4405.0 1710.90  4454.3 1709.55  4489.9 1710.68
  4560.6 1709.19  4624.2 1709.01  4709.1 1710.04  4758.5 1709.07  4825.8 1709.75
  4916.0 1706.16  4983.4 1705.66  4983.9 1705.16  4988.8 1705.66  5206.6 1707.28
  5246.6 1708.63  5331.1 1708.13  5352.6 1709.26  5368.4 1708.02  5374.2 1708.90
  5390.0 1707.49  5433.1 1708.05  5498.0 1706.47  5625.0 1706.54  5682.7 1707.30
  5711.7 1708.66  5733.3 1708.39  5792.2 1712.23  5798.1 1711.00  5819.8 1710.69
#Mann=3,-1,0
  4292.5    0.05       0  4983.4    0.05       0  4988.8    0.05       0
Bank Sta=4983.4,4988.8
Exp/Cntr=0.3,0.1

Type RM Length L Ch R = 1,4268,77,77,77
BEGIN DESCRIPTION:
Mapping XS 5fda2a51
END DESCRIPTION:
XS GIS Cut Line= 3
      1570630.10      6922731.73      1570262.89      6922395.77
      1569533.72      6921729.10
#Sta/Elev= 30
  3842.7 1711.46  3870.2 1712.31  3912.7 1711.97  3962.1 1710.16  4075.6 1711.62
  4118.1 1709.62  4174.8 1708.77  4238.4 1709.69  4309.3 1707.35  4393.7 1708.56
  4457.9 1707.84  4528.2 1710.55  4592.3 1710.46  4613.3 1708.90  4662.7 1707.73
  4741.0 1707.86  4811.8 1706.83  4882.2 1708.19  4946.3 1706.40  5013.9 1706.11
  5014.3 1705.61  5019.4 1706.11  5109.1 1707.47  5115.9 1706.79  5165.2 1707.68
  5172.6 1707.12  5236.2 1710.05  5243.6 1709.48  5286.0 1710.99  5328.4 1710.86
#Mann=3,-1,0
  3842.7    0.05       0  5013.9    0.05       0  5019.4    0.05       0
Bank Sta=5013.9,5019.4
Exp/Cntr=0.3,0.1

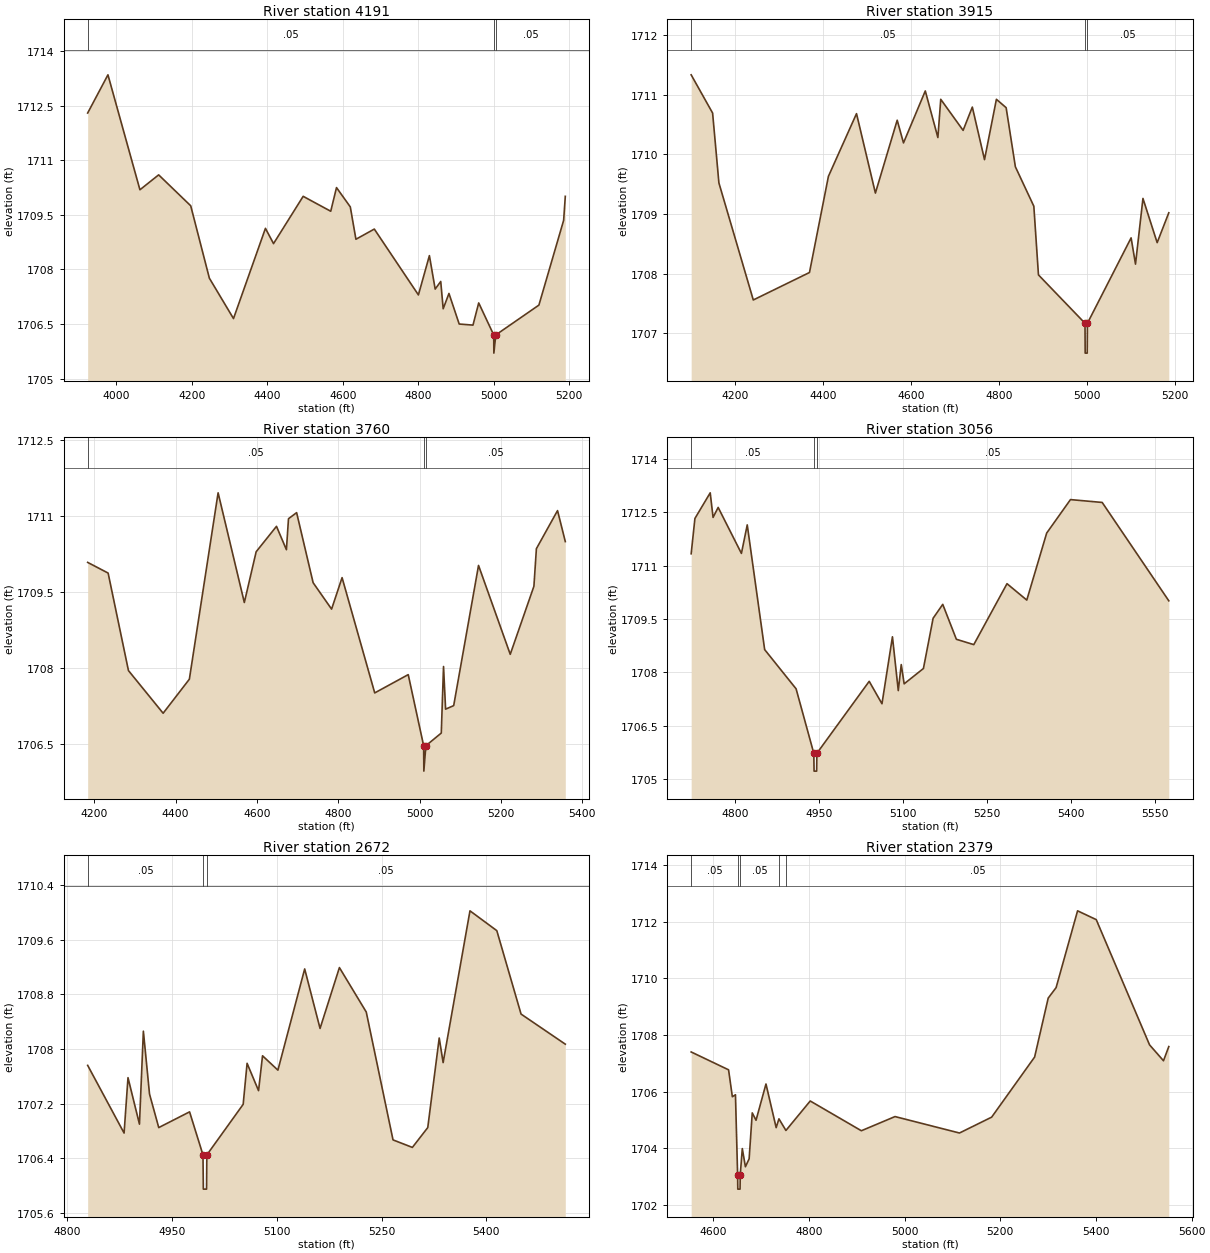
Type RM Length L Ch R = 1,4191,276,276,276
BEGIN DESCRIPTION:
Mapping XS 083b0e5c
END DESCRIPTION:
XS GIS Cut Line= 3
      1570645.52      6922533.20      1570279.07      6922186.24
      1569635.91      6921780.85
#Sta/Elev= 30
  3924.6 1712.30  3978.3 1713.35  4063.0 1710.19  4112.6 1710.60  4197.5 1709.75
  4246.9 1707.76  4310.8 1706.65  4395.4 1709.13  4416.8 1708.71  4495.3 1710.01
  4568.3 1709.60  4583.6 1710.25  4620.1 1709.72  4635.0 1708.83  4683.7 1709.11
  4800.5 1707.30  4829.6 1708.38  4844.9 1707.46  4859.6 1707.67  4866.1 1706.92
  4881.4 1707.34  4908.5 1706.50  4945.0 1706.47  4960.2 1707.08  4999.9 1706.20
  5000.3 1705.70  5005.4 1706.20  5119.6 1707.02  5185.1 1709.35  5189.5 1710.01
#Mann=3,-1,0
  3924.6    0.05       0  4999.9    0.05       0  5005.4    0.05       0
Bank Sta=4999.9,5005.4
Exp/Cntr=0.3,0.1

Type RM Length L Ch R = 1,3915,155,155,155
BEGIN DESCRIPTION:
Mapping XS df6c2622
END DESCRIPTION:
XS GIS Cut Line= 3
      1570580.58      6922351.49      1570070.18      6921927.02
      1569942.57      6921525.97
#Sta/Elev= 30
  4101.2 1711.33  4149.9 1710.69  4164.2 1709.52  4242.3 1707.56  4369.9 1708.02
  4412.9 1709.63  4476.7 1710.68  4519.6 1709.35  4569.1 1710.57  4583.4 1710.19
  4632.9 1711.06  4661.5 1710.28  4668.0 1710.92  4718.8 1710.40  4739.7 1710.79
  4767.4 1709.91  4794.4 1710.92  4816.5 1710.78  4837.5 1709.79  4879.4 1709.13
  4889.9 1707.98  4995.6 1707.17  4996.0 1706.67  5000.6 1706.67  5001.1 1707.17
  5100.3 1708.60  5110.3 1708.16  5127.2 1709.26  5159.5 1708.52  5185.9 1709.02
#Mann=3,-1,0
  4101.2    0.05       0  4995.6    0.03       0  5001.1    0.05       0
Bank Sta=4995.6,5001.1
Exp/Cntr=0.3,0.1

Type RM Length L Ch R = 1,3760,704,704,704
BEGIN DESCRIPTION:
Mapping XS 05a47303
END DESCRIPTION:
XS GIS Cut Line= 3
      1570588.45      6922304.65      1570213.41      6922020.77
      1570085.81      6921328.09
#Sta/Elev= 30
  4183.7 1710.08  4234.0 1709.87  4284.0 1707.95  4369.3 1707.11  4433.8 1707.78
  4504.5 1711.45  4569.0 1709.29  4598.1 1710.29  4648.1 1710.79  4672.5 1710.33
  4677.6 1710.94  4697.6 1711.06  4738.2 1709.68  4783.6 1709.16  4809.4 1709.78
  4889.7 1707.51  4972.1 1707.87  5010.0 1706.47  5010.5 1705.97  5015.5 1706.47
  5053.4 1706.72  5058.9 1708.03  5064.0 1707.19  5083.9 1707.26  5145.0 1710.02
  5223.0 1708.27  5281.2 1709.61  5287.3 1710.35  5339.3 1711.10  5358.4 1710.49
#Mann=3,-1,0
  4183.7    0.05       0  5010.0    0.03       0  5015.5    0.05       0
Bank Sta=5010,5015.5
Exp/Cntr=0.3,0.1

Type RM Length L Ch R = 1,3056,384,384,384
BEGIN DESCRIPTION:
Mapping XS b05af530
END DESCRIPTION:
XS GIS Cut Line= 3
      1570799.34      6922114.48      1570661.33      6921611.92
      1570432.44      6921372.22
#Sta/Elev= 30
  4722.2 1711.33  4728.9 1712.32  4756.2 1713.04  4761.3 1712.35  4770.4 1712.63
  4811.9 1711.34  4822.3 1712.14  4853.4 1708.64  4909.5 1707.54  4941.1 1705.73
  4941.6 1705.23  4946.2 1705.23  4946.6 1705.73  5040.0 1707.75  5062.8 1707.12
  5081.5 1709.00  5091.9 1707.49  5097.2 1708.22  5102.4 1707.68  5136.8 1708.11
  5154.1 1709.52  5171.3 1709.91  5195.6 1708.93  5226.7 1708.78  5286.0 1710.49
  5321.3 1710.03  5356.8 1711.91  5399.3 1712.85  5455.9 1712.77  5574.8 1710.01
#Mann=3,-1,0
  4722.2    0.05       0  4941.1    0.05       0  4946.6    0.05       0
Bank Sta=4941.1,4946.6
Exp/Cntr=0.3,0.1

Type RM Length L Ch R = 1,2672,293,293,293
BEGIN DESCRIPTION:
Mapping XS 8c2dfa2e
END DESCRIPTION:
XS GIS Cut Line= 2
      1571113.23      6921628.81      1570509.04      6921309.45
#Sta/Elev= 30
  4829.5 1707.76  4881.6 1706.77  4887.2 1707.58  4903.6 1706.90  4909.2 1708.26
  4918.0 1707.34  4931.2 1706.85  4975.3 1707.08  4994.5 1706.45  4995.0 1705.95
  4999.6 1705.95  5000.0 1706.45  5052.0 1707.19  5057.6 1707.79  5074.0 1707.39
  5079.7 1707.90  5101.7 1707.69  5140.0 1709.17  5162.0 1708.30  5189.7 1709.19
  5228.1 1708.54  5266.4 1706.67  5294.1 1706.56  5316.1 1706.85  5332.5 1708.16
  5338.1 1707.80  5376.5 1710.02  5414.9 1709.73  5449.6 1708.51  5512.9 1708.07
#Mann=3,-1,0
  4829.5    0.05       0  4994.5    0.05       0  5000.0    0.05       0
Bank Sta=4994.5,5000
Exp/Cntr=0.3,0.1

Type RM Length L Ch R = 1,2379,231,231,231
BEGIN DESCRIPTION:
Mapping XS c29d987a
END DESCRIPTION:
XS GIS Cut Line= 3
      1571262.06      6921561.37      1570940.27      6921295.95
      1570418.93      6921038.67
#Sta/Elev= 30
  4553.7 1707.40  4631.9 1706.77  4639.8 1705.82  4646.3 1705.89  4650.8 1703.06
  4651.2 1702.56  4655.9 1702.56  4656.3 1703.06  4660.6 1703.99  4667.1 1703.35
  4674.9 1703.63  4681.4 1705.25  4689.3 1704.99  4710.1 1706.27  4731.4 1704.73
  4737.2 1705.04  4751.8 1704.63  4802.6 1705.67  4909.5 1704.62  4979.9 1705.12
  5114.6 1704.54  5181.9 1705.10  5271.7 1707.22  5300.1 1709.30  5316.6 1709.67
  5361.5 1712.38  5400.5 1712.07  5512.0 1707.65  5541.1 1707.09  5552.2 1707.59
#Mann=5,-1,0
  4553.7    0.05       0  4650.8    0.05       0  4656.3    0.05       0
  4737.2    0.12       0  4751.8    0.05       0
Bank Sta=4650.8,4656.3
Exp/Cntr=0.3,0.1

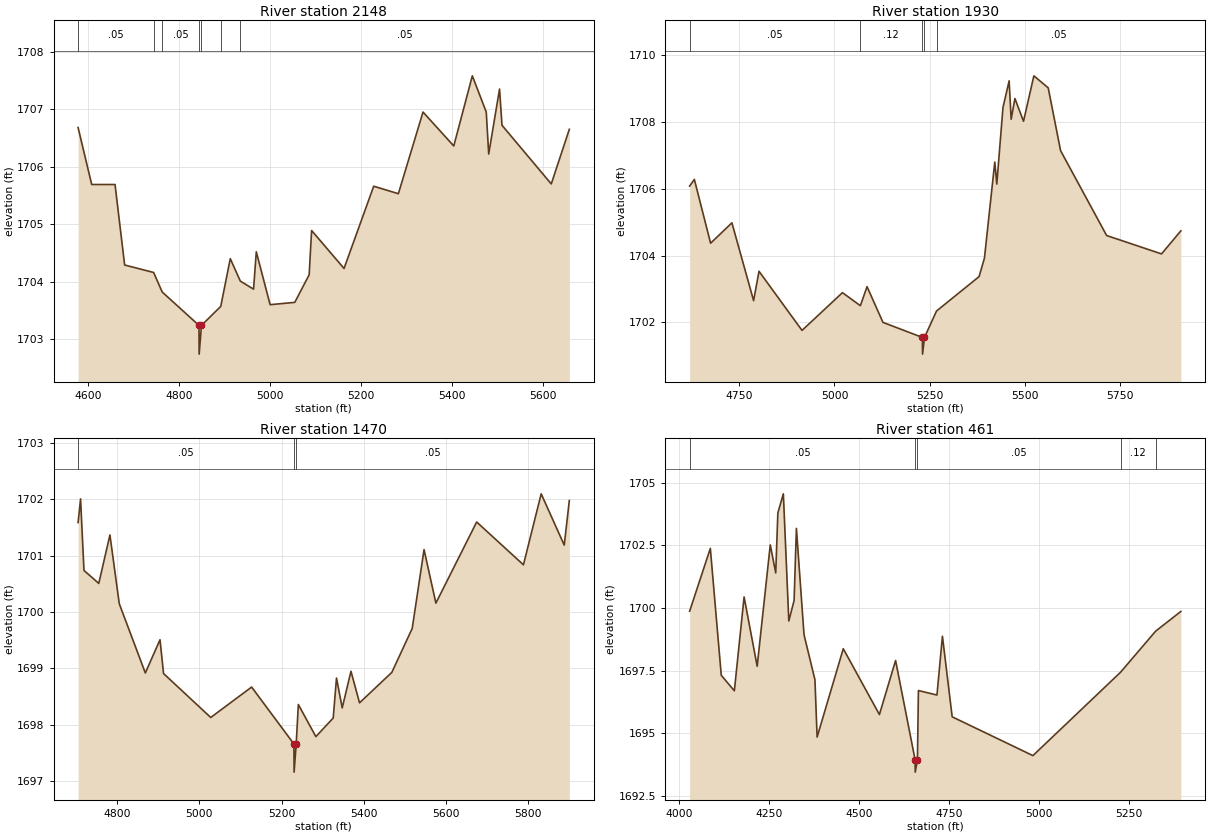
Type RM Length L Ch R = 1,2148,218,218,218
BEGIN DESCRIPTION:
Mapping XS 37e85f64
END DESCRIPTION:
XS GIS Cut Line= 3
      1571409.51      6921336.46      1571070.37      6921114.27
      1570448.35      6920853.80
#Sta/Elev= 30
  4578.1 1706.68  4608.0 1705.69  4659.3 1705.69  4680.4 1704.29  4744.1 1704.16
  4763.0 1703.82  4843.8 1703.24  4844.2 1702.74  4849.3 1703.24  4891.7 1703.57
  4912.6 1704.40  4934.7 1704.01  4963.8 1703.87  4969.8 1704.52  5000.2 1703.60
  5054.4 1703.64  5086.0 1704.12  5091.4 1704.89  5162.7 1704.23  5227.9 1705.66
  5282.1 1705.53  5336.3 1706.95  5403.9 1706.36  5444.7 1707.58  5475.3 1706.95
  5480.7 1706.22  5504.5 1707.35  5509.9 1706.72  5618.2 1705.70  5657.9 1706.65
#Mann=7,-1,0
  4578.1    0.05       0  4744.1    0.12       0  4763.0    0.05       0
  4843.8    0.05       0  4849.3    0.05       0  4891.7    0.12       0
  4934.7    0.05       0
Bank Sta=4843.8,4849.3
Exp/Cntr=0.3,0.1

Type RM Length L Ch R = 1,1930,460,460,460
BEGIN DESCRIPTION:
Mapping XS 0ca745a9
END DESCRIPTION:
XS GIS Cut Line= 3
      1571457.02      6921223.13      1570952.02      6920783.90
      1570358.85      6920598.68
#Sta/Elev= 30
  4619.4 1706.08  4631.8 1706.28  4674.5 1704.37  4730.5 1704.98  4787.5 1702.65
  4801.7 1703.53  4914.7 1701.76  5021.0 1702.89  5068.0 1702.50  5085.6 1703.07
  5127.4 1702.00  5230.9 1701.55  5231.4 1701.05  5236.5 1701.55  5268.1 1702.34
  5379.9 1703.37  5394.0 1703.92  5421.2 1706.80  5426.5 1706.14  5442.7 1708.43
  5458.9 1709.23  5464.2 1708.08  5474.1 1708.70  5496.7 1708.02  5523.9 1709.38
  5561.6 1709.02  5594.1 1707.14  5715.1 1704.60  5859.3 1704.05  5910.1 1704.74
#Mann=5,-1,0
  4619.4    0.05       0  5068.0    0.12       0  5230.9    0.05       0
  5236.5    0.12       0  5268.1    0.05       0
Bank Sta=5230.9,5236.5
Exp/Cntr=0.3,0.1

Type RM Length L Ch R = 1,1470,1009,1009,1009
BEGIN DESCRIPTION:
Mapping XS 09baefca
END DESCRIPTION:
XS GIS Cut Line= 3
      1571492.27      6920889.63      1571309.04      6920631.22
      1570624.03      6920082.28
#Sta/Elev= 30
  4705.0 1701.59  4711.0 1702.01  4719.3 1700.74  4755.3 1700.51  4782.4 1701.37
  4805.1 1700.15  4868.5 1698.92  4904.2 1699.51  4912.8 1698.91  5027.6 1698.13
  5127.0 1698.67  5229.8 1697.66  5230.3 1697.16  5235.4 1697.66  5240.6 1698.36
  5283.2 1697.79  5325.4 1698.12  5333.4 1698.83  5347.3 1698.30  5368.6 1698.95
  5389.4 1698.39  5467.9 1698.93  5517.5 1699.71  5546.3 1701.11  5575.1 1700.16
  5674.3 1701.60  5788.0 1700.84  5831.2 1702.10  5887.2 1701.19  5899.6 1701.98
#Mann=3,-1,0
  4705.0    0.05       0  5229.8    0.03       0  5235.4    0.05       0
Bank Sta=5229.8,5235.4
Exp/Cntr=0.3,0.1

Type RM Length L Ch R = 1,461,0,0,0
BEGIN DESCRIPTION:
Deadman 22 1.0
END DESCRIPTION:
XS GIS Cut Line= 3
      1572680.02      6920613.01      1571861.09      6920090.55
      1571580.02      6919813.02
#Sta/Elev= 30
  4028.6 1699.87  4086.2 1702.38  4116.6 1697.31  4153.0 1696.69  4180.1 1700.44
  4216.5 1697.67  4252.9 1702.52  4268.1 1701.40  4274.0 1703.79  4289.3 1704.56
  4304.5 1699.48  4319.2 1700.30  4325.6 1703.18  4346.8 1698.93  4377.2 1697.13
  4383.2 1694.84  4456.0 1698.37  4556.5 1695.74  4601.5 1697.90  4655.7 1693.94
  4656.2 1693.44  4662.3 1693.94  4665.0 1696.70  4716.6 1696.52  4731.8 1698.87
  4758.9 1695.65  4983.5 1694.10  5227.2 1697.43  5324.7 1699.07  5395.0 1699.86
#Mann=5,-1,0
  4028.6    0.05       0  4655.7    0.05       0  4662.3    0.05       0
  5227.2    0.12       0  5324.7    0.05       0
Bank Sta=4655.7,4662.3
Exp/Cntr=0.3,0.1

Chan Stop Cuts=-1