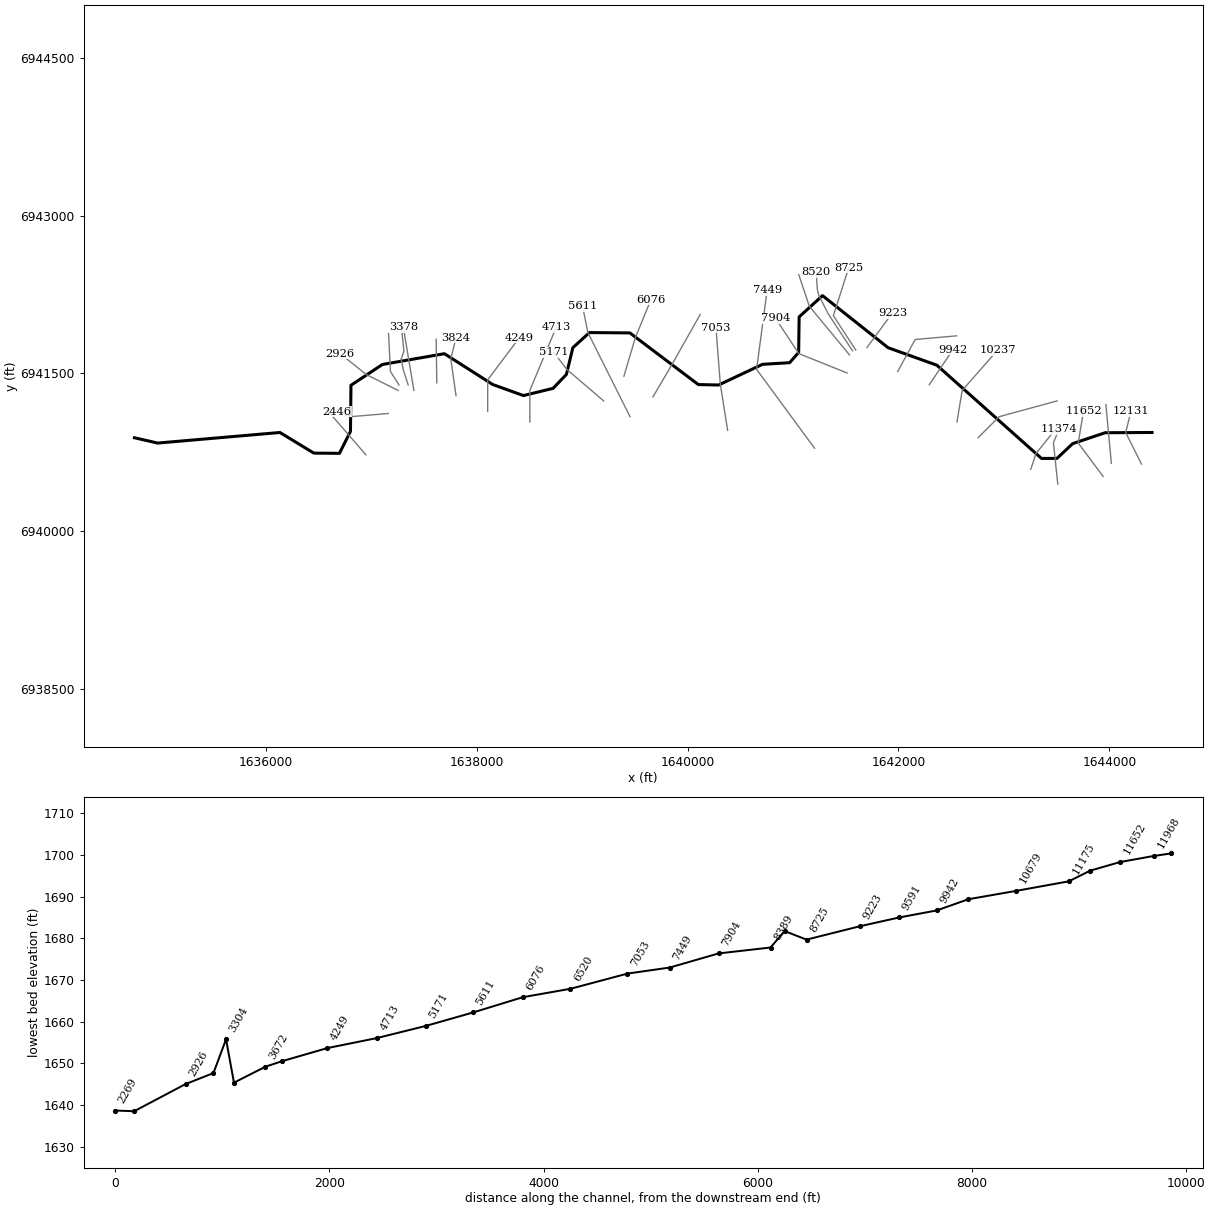
--- Deadman 23.prj (project) ---

Proj Title=Deadman 23 Base Level Engineering
Current Plan=p01
Default Exp/Contr=0.3,0.1
English Units
Geom File=g01
Flow File=f01
Plan File=p01
BEGIN DESCRIPTION:
Deadman 23
END DESCRIPTION:

--- Deadman 23.p01 (plan) ---

Plan Title=Multiple Run
Short Identifier=Multiple
Geom File=g01
Flow File=f01
Subcritical Flow
K Sum by GR= 0
Std Step Tol= 0.01
Critical Tol= 0.01
Num of Std Step Trials= 20
Max Error Tol= 0.3
Flow Tol Ratio= 0.001
Split Flow NTrial= 30
Split Flow Tol= 0.02
Split Flow Ratio= 0.02
Log Output Level= 0
Friction Slope Method= 1
Unsteady Friction Slope Method= 2
Unsteady Bridges Friction Slope Method= 1
Parabolic Critical Depth
Global Vel Dist=  1 , 1 , 1
Global Log Level= 0
CheckData=True
Encroach Param= -1, 0, 0, 0
BEGIN DESCRIPTION:
Multiple Run
END DESCRIPTION:

--- Deadman 23.f01 (steady flow) ---

Flow Title=Multiple
Number of Profiles=7
Profile Names=10-year,25-year,50-year,1pct_min,100-year,1pct_plu,500-year
River Rch & RM= Deadman 23,Reach-1,12131
     361     510     634     393     784    1564    1213
River Rch & RM= Deadman 23,Reach-1,7053
     419     594     741     460     919    1833    1430
Boundary for River Rch & Prof#=Deadman 23,Reach-1,1
Up Type=0
Dn Type=3
Dn Slope=0.015
Boundary for River Rch & Prof#=Deadman 23,Reach-1,2
Up Type=0
Dn Type=3
Dn Slope=0.015
Boundary for River Rch & Prof#=Deadman 23,Reach-1,3
Up Type=0
Dn Type=3
Dn Slope=0.015
Boundary for River Rch & Prof#=Deadman 23,Reach-1,4
Up Type=0
Dn Type=3
Dn Slope=0.015
Boundary for River Rch & Prof#=Deadman 23,Reach-1,5
Up Type=0
Dn Type=3
Dn Slope=0.015
Boundary for River Rch & Prof#=Deadman 23,Reach-1,6
Up Type=0
Dn Type=3
Dn Slope=0.015
Boundary for River Rch & Prof#=Deadman 23,Reach-1,7
Up Type=0
Dn Type=3
Dn Slope=0.015

--- Deadman 23.g01 (geometry) ---

Geom Title=Existing Conditions

River Reach=Deadman 23,Reach-1
Reach XY= 30
      1644405.00      6940938.00      1643960.94      6940935.74
      1643652.70      6940832.17      1643503.53      6940691.53
      1643356.47      6940691.53      1642364.68      6941577.24
      1641902.55      6941743.47      1641280.00      6942238.59
      1641058.54      6942036.54      1641053.96      6941698.43
      1640968.35      6941601.36      1640710.94      6941585.74
      1640294.50      6941389.22      1640102.55      6941393.47
      1639453.45      6941884.25      1639070.16      6941887.62
      1638912.88      6941744.13      1638851.45      6941489.47
      1638725.17      6941357.60      1638444.31      6941288.77
      1638152.71      6941393.84      1637694.49      6941686.78
      1637106.56      6941584.24      1636808.53      6941386.55
      1636803.78      6940948.50      1636699.35      6940739.97
      1636456.55      6940741.75      1636134.97      6940937.94
      1634975.05      6940837.40      1634755.00      6940888.00

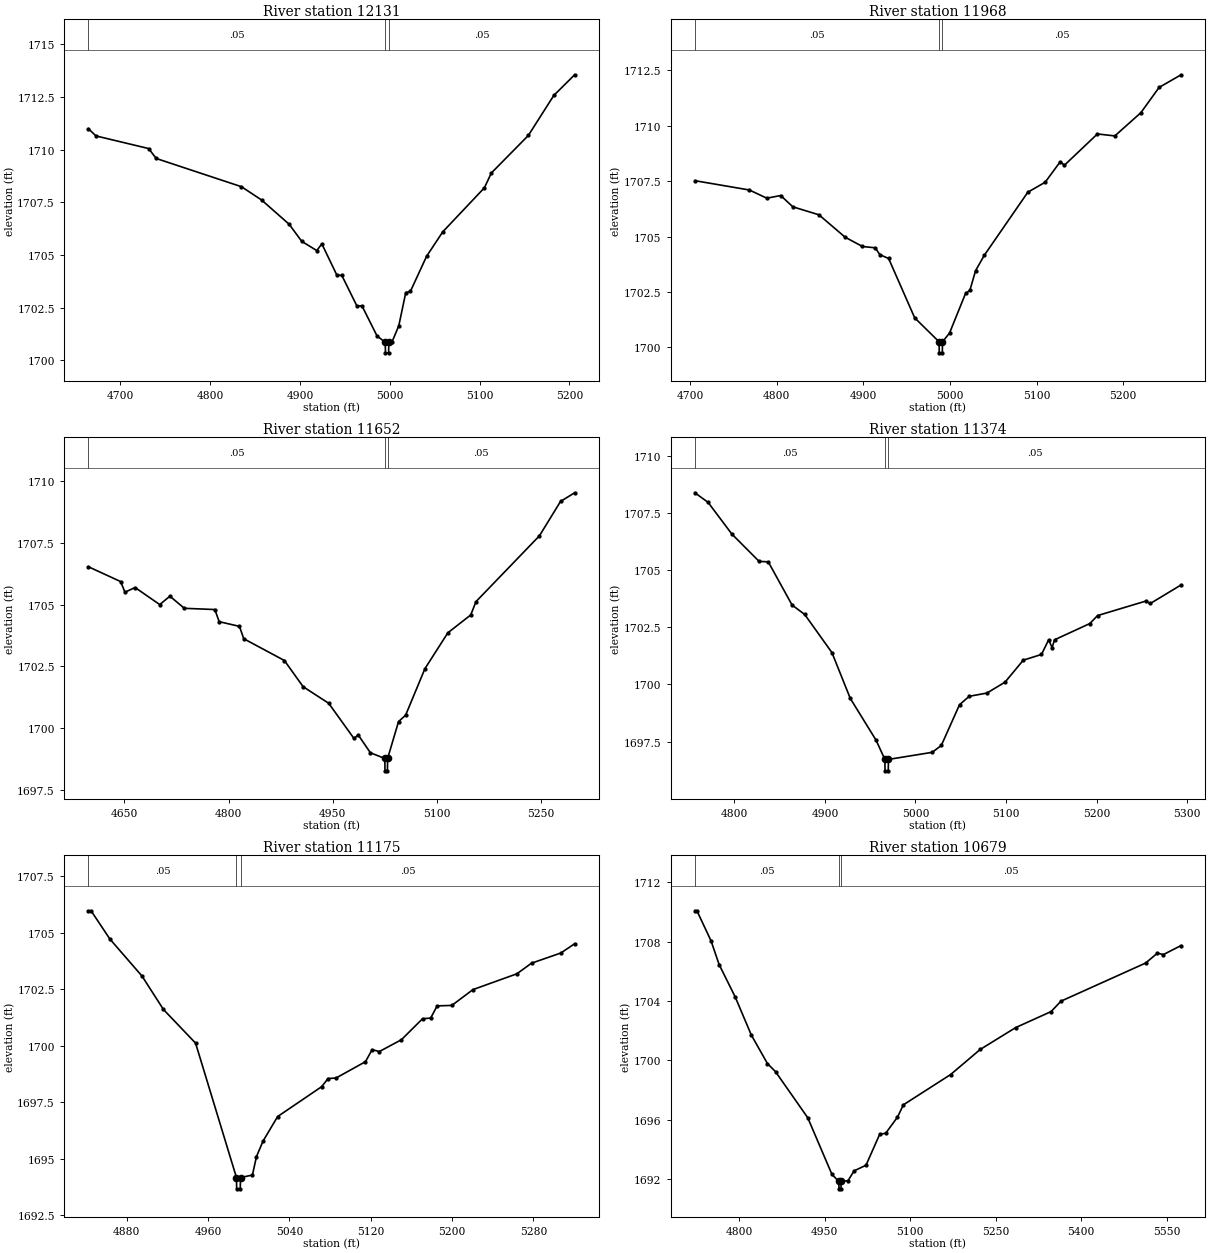
Type RM Length L Ch R = 1,12131,163,163,163
BEGIN DESCRIPTION:
Deadman 23 23.0
END DESCRIPTION:
XS GIS Cut Line= 3
      1644305.01      6940637.98      1644155.00      6940938.00
      1644205.00      6941138.01
#Sta/Elev= 30
  4664.3 1710.99  4672.7 1710.65  4731.4 1710.05  4739.8 1709.58  4834.8 1708.24
  4857.2 1707.61  4887.9 1706.46  4901.9 1705.65  4918.7 1705.21  4924.3 1705.53
  4941.0 1704.05  4946.6 1704.03  4963.4 1702.58  4969.0 1702.59  4985.8 1701.16
  4994.9 1700.86  4995.2 1700.36  4998.7 1700.36  4998.9 1700.86  5002.3 1700.86
  5010.0 1701.64  5017.8 1703.22  5022.9 1703.27  5041.0 1704.94  5059.0 1706.10
  5105.4 1708.19  5113.1 1708.89  5154.3 1710.67  5182.7 1712.57  5205.9 1713.55
#Mann=3,-1,0
  4664.3    0.05       0  4994.9    0.03       0  4998.9    0.05       0
Bank Sta=4994.9,4998.9
Exp/Cntr=0.3,0.1

Type RM Length L Ch R = 1,11968,316,316,316
BEGIN DESCRIPTION:
Mapping XS d7dac541
END DESCRIPTION:
XS GIS Cut Line= 2
      1644019.25      6940645.39      1643967.27      6941204.18
#Sta/Elev= 30
  4705.7 1707.52  4768.6 1707.10  4788.7 1706.73  4804.7 1706.85  4818.8 1706.34
  4848.9 1705.98  4879.1 1704.97  4899.1 1704.55  4913.9 1704.49  4919.2 1704.18
  4929.3 1704.01  4959.4 1701.33  4987.5 1700.25  4987.8 1699.75  4991.3 1699.75
  4991.5 1700.25  4999.6 1700.64  5018.1 1702.43  5023.1 1702.57  5029.7 1703.46
  5039.7 1704.15  5090.0 1707.00  5110.0 1707.45  5127.3 1708.37  5132.3 1708.22
  5170.3 1709.63  5190.4 1709.54  5220.5 1710.59  5241.5 1711.73  5266.9 1712.30
#Mann=3,-1,0
  4705.7    0.05       0  4987.5    0.03       0  4991.5    0.05       0
Bank Sta=4987.5,4991.5
Exp/Cntr=0.3,0.1

Type RM Length L Ch R = 1,11652,278,278,278
BEGIN DESCRIPTION:
Deadman 23 22.0
END DESCRIPTION:
XS GIS Cut Line= 3
      1643941.12      6940520.42      1643705.00      6940838.00
      1643755.00      6941138.02
#Sta/Elev= 30
  4598.3 1706.53  4644.7 1705.93  4650.9 1705.50  4665.5 1705.69  4701.0 1705.00
  4715.6 1705.34  4736.4 1704.85  4780.3 1704.80  4786.5 1704.31  4815.7 1704.12
  4821.9 1703.62  4880.4 1702.74  4907.4 1701.68  4944.2 1701.01  4980.5 1699.59
  4986.7 1699.73  5004.2 1699.01  5025.0 1698.78  5025.2 1698.28  5028.7 1698.28
  5029.0 1698.78  5044.7 1700.27  5054.9 1700.53  5082.7 1702.41  5115.7 1703.86
  5148.6 1704.58  5156.2 1705.12  5247.5 1707.78  5277.9 1709.17  5298.2 1709.52
#Mann=3,-1,0
  4598.3    0.05       0  5025.0    0.03       0  5029.0    0.05       0
Bank Sta=5025,5029
Exp/Cntr=0.3,0.1

Type RM Length L Ch R = 1,11374,199,199,199
BEGIN DESCRIPTION:
Mapping XS 6033a365
END DESCRIPTION:
XS GIS Cut Line= 3
      1643511.44      6940447.49      1643469.77      6940840.73
      1643524.47      6940970.97
#Sta/Elev= 30
  4756.5 1708.38  4771.1 1707.96  4797.2 1706.58  4827.4 1705.38  4837.5 1705.36
  4863.8 1703.47  4877.7 1703.06  4907.8 1701.39  4928.0 1699.39  4956.5 1697.56
  4966.2 1696.72  4966.4 1696.22  4969.9 1696.22  4970.2 1696.72  5018.5 1697.03
  5028.5 1697.33  5048.6 1699.11  5059.3 1699.48  5078.8 1699.62  5098.9 1700.10
  5119.0 1701.06  5139.1 1701.31  5147.0 1701.95  5150.8 1701.61  5153.5 1701.95
  5192.4 1702.66  5201.0 1703.01  5253.9 1703.64  5259.3 1703.54  5293.2 1704.35
#Mann=3,-1,0
  4756.5    0.05       0  4966.2    0.03       0  4970.2    0.05       0
Bank Sta=4966.2,4970.2
Exp/Cntr=0.3,0.1

Type RM Length L Ch R = 1,11175,496,496,496
BEGIN DESCRIPTION:
Deadman 23 21.0
END DESCRIPTION:
XS GIS Cut Line= 3
      1643255.01      6940588.02      1643305.00      6940738.00
      1643504.97      6940987.96
#Sta/Elev= 30
  4842.4 1705.97  4845.0 1705.97  4863.5 1704.72  4895.1 1703.08  4916.2 1701.60
  4947.8 1700.11  4988.0 1694.16  4988.2 1693.66  4991.7 1693.66  4992.0 1694.16
  5003.7 1694.27  5007.7 1695.09  5014.1 1695.77  5028.5 1696.86  5071.7 1698.18
  5078.1 1698.54  5086.1 1698.57  5114.9 1699.29  5121.4 1699.82  5128.6 1699.74
  5150.2 1700.26  5171.0 1701.19  5179.0 1701.22  5185.4 1701.76  5199.8 1701.78
  5220.6 1702.48  5263.8 1703.18  5278.2 1703.65  5307.0 1704.10  5320.6 1704.51
#Mann=3,-1,0
  4842.4    0.05       0  4988.0    0.03       0  4992.0    0.05       0
Bank Sta=4988,4992
Exp/Cntr=0.3,0.1

Type RM Length L Ch R = 1,10679,442,442,442
BEGIN DESCRIPTION:
Deadman 23 20.0
END DESCRIPTION:
XS GIS Cut Line= 3
      1642754.97      6940887.97      1642955.00      6941088.00
      1643505.03      6941238.01
#Sta/Elev= 30
  4722.3 1710.08  4725.9 1710.08  4750.6 1708.06  4764.8 1706.46  4793.1 1704.27
  4821.3 1701.71  4849.6 1699.79  4863.8 1699.24  4920.3 1696.14  4962.8 1692.32
  4974.9 1691.85  4975.1 1691.35  4978.6 1691.35  4978.9 1691.85  4991.0 1691.90
  5001.6 1692.56  5022.5 1692.94  5046.6 1695.03  5057.0 1695.09  5077.7 1696.18
  5088.1 1697.01  5171.0 1699.05  5222.9 1700.74  5285.0 1702.21  5347.2 1703.29
  5364.5 1703.99  5513.1 1706.56  5533.8 1707.23  5544.2 1707.13  5575.3 1707.74
#Mann=3,-1,0
  4722.3    0.05       0  4974.9    0.03       0  4978.9    0.05       0
Bank Sta=4974.9,4978.9
Exp/Cntr=0.3,0.1

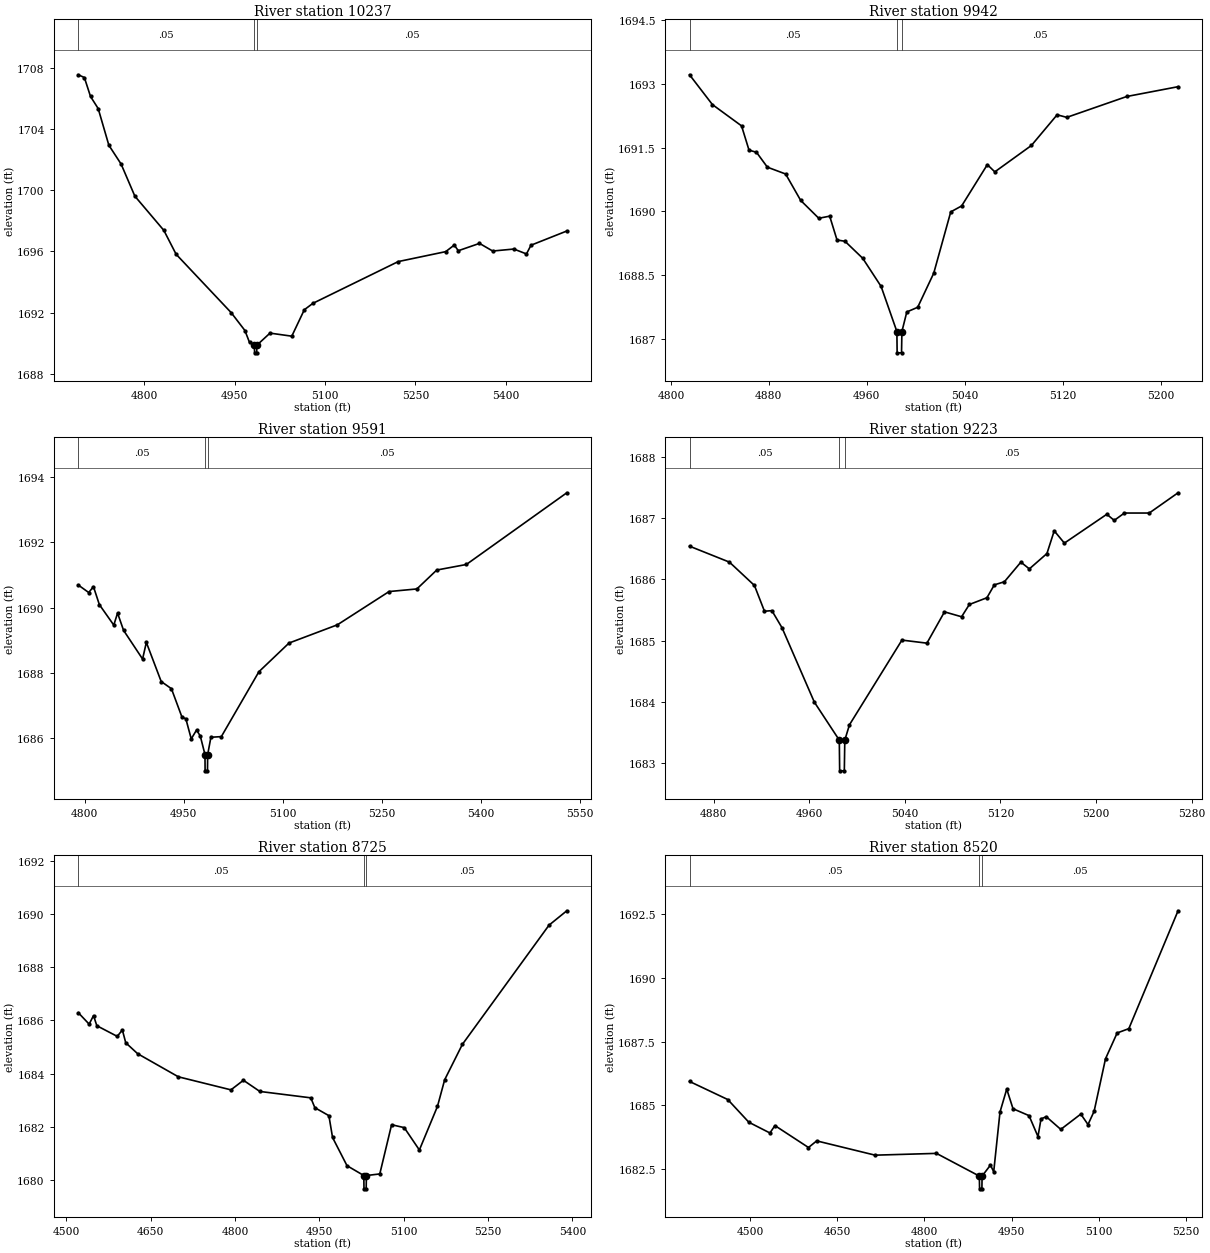
Type RM Length L Ch R = 1,10237,295,295,295
BEGIN DESCRIPTION:
Deadman 23 19.0
END DESCRIPTION:
XS GIS Cut Line= 3
      1642555.00      6941037.99      1642605.00      6941338.00
      1642938.52      6941718.33
#Sta/Elev= 30
  4690.9 1707.56  4701.0 1707.38  4711.2 1706.14  4723.9 1705.35  4741.6 1702.95
  4761.9 1701.72  4784.7 1699.62  4832.8 1697.38  4853.1 1695.82  4944.4 1692.00
  4967.2 1690.83  4974.8 1690.05  4982.9 1689.87  4983.2 1689.37  4986.7 1689.37
  4987.0 1689.87  5008.8 1690.66  5044.9 1690.46  5065.7 1692.19  5080.0 1692.61
  5221.4 1695.34  5300.1 1695.99  5314.3 1696.42  5321.0 1696.05  5356.1 1696.53
  5378.0 1696.03  5413.1 1696.16  5434.0 1695.84  5441.5 1696.41  5500.9 1697.34
#Mann=3,-1,0
  4690.9    0.05       0  4982.9    0.03       0  4987.0    0.05       0
Bank Sta=4982.9,4987
Exp/Cntr=0.3,0.1

Type RM Length L Ch R = 1,9942,351,351,351
BEGIN DESCRIPTION:
Mapping XS a463c98a
END DESCRIPTION:
XS GIS Cut Line= 2
      1642292.69      6941392.81      1642516.46      6941723.27
#Sta/Elev= 30
  4815.2 1693.21  4833.9 1692.51  4857.7 1692.01  4863.8 1691.44  4869.9 1691.39
  4878.8 1691.04  4893.7 1690.88  4906.0 1690.26  4920.8 1689.84  4929.7 1689.89
  4935.7 1689.33  4942.2 1689.30  4956.7 1688.90  4971.7 1688.24  4984.6 1687.18
  4984.8 1686.68  4988.4 1686.68  4988.7 1687.18  4992.7 1687.64  5001.6 1687.75
  5014.7 1688.55  5028.6 1689.99  5037.5 1690.13  5058.5 1691.10  5064.6 1690.93
  5094.5 1691.55  5115.5 1692.27  5123.4 1692.21  5172.4 1692.70  5214.3 1692.93
#Mann=3,-1,0
  4815.2    0.05       0  4984.6    0.03       0  4988.7    0.05       0
Bank Sta=4984.6,4988.7
Exp/Cntr=0.3,0.1

Type RM Length L Ch R = 1,9591,368,368,368
BEGIN DESCRIPTION:
Mapping XS 3e7e99d4
END DESCRIPTION:
XS GIS Cut Line= 3
      1641993.19      6941517.77      1642159.00      6941821.77
      1642551.19      6941856.44
#Sta/Elev= 30
  4790.5 1690.69  4806.3 1690.46  4813.5 1690.64  4822.4 1690.09  4844.3 1689.46
  4850.0 1689.83  4859.1 1689.30  4887.9 1688.42  4893.6 1688.93  4916.1 1687.73
  4931.6 1687.51  4947.7 1686.63  4953.4 1686.59  4961.6 1685.97  4969.6 1686.24
  4975.3 1686.06  4982.4 1685.49  4982.6 1684.99  4986.2 1684.99  4986.5 1685.49
  4991.4 1686.02  5007.2 1686.04  5064.1 1688.03  5109.7 1688.91  5183.0 1689.47
  5261.3 1690.49  5303.4 1690.57  5333.5 1691.15  5378.3 1691.32  5530.5 1693.52
#Mann=3,-1,0
  4790.5    0.05       0  4982.4    0.03       0  4986.5    0.05       0
Bank Sta=4982.4,4986.5
Exp/Cntr=0.3,0.1

Type RM Length L Ch R = 1,9223,498,498,498
BEGIN DESCRIPTION:
Mapping XS 9e2b5a65
END DESCRIPTION:
XS GIS Cut Line= 2
      1641701.52      6941744.34      1641942.98      6942074.08
#Sta/Elev= 30
  4859.9 1686.54  4893.3 1686.28  4914.2 1685.90  4922.6 1685.48  4928.8 1685.49
  4937.3 1685.21  4964.3 1684.00  4985.2 1683.38  4985.5 1682.88  4989.4 1682.88
  4989.8 1683.38  4993.7 1683.63  5037.6 1685.01  5058.5 1684.96  5073.2 1685.47
  5087.5 1685.39  5094.0 1685.59  5108.7 1685.70  5114.9 1685.91  5123.3 1685.96
  5137.1 1686.28  5144.2 1686.17  5158.9 1686.42  5165.0 1686.79  5173.5 1686.59
  5209.0 1687.06  5215.2 1686.96  5223.7 1687.08  5244.5 1687.08  5268.6 1687.41
#Mann=3,-1,0
  4859.9    0.05       0  4985.2    0.03       0  4989.8    0.05       0
Bank Sta=4985.2,4989.8
Exp/Cntr=0.3,0.1

Type RM Length L Ch R = 1,8725,205,205,205
BEGIN DESCRIPTION:
Mapping XS 9702ac05
END DESCRIPTION:
XS GIS Cut Line= 3
      1641595.72      6941721.79      1641383.29      6942048.38
      1641529.08      6942504.87
#Sta/Elev= 30
  4521.1 1686.29  4540.4 1685.86  4548.2 1686.18  4554.1 1685.80  4590.4 1685.40
  4599.5 1685.64  4605.5 1685.16  4626.6 1684.75  4699.1 1683.88  4792.6 1683.39
  4814.8 1683.75  4844.0 1683.33  4934.6 1683.09  4941.8 1682.72  4966.8 1682.42
  4973.3 1681.60  4999.0 1680.54  5028.9 1680.17  5029.2 1679.67  5033.1 1679.67
  5033.5 1680.17  5057.3 1680.23  5078.3 1682.08  5100.8 1681.97  5127.7 1681.13
  5159.9 1682.77  5172.7 1683.77  5204.2 1685.10  5358.3 1689.58  5389.9 1690.12
#Mann=3,-1,0
  4521.1    0.05       0  5028.9    0.05       0  5033.5    0.05       0
Bank Sta=5028.9,5033.5
Exp/Cntr=0.3,0.1

Type RM Length L Ch R = 1,8520,131,131,131
BEGIN DESCRIPTION:
Mapping XS c3b60624
END DESCRIPTION:
XS GIS Cut Line= 6
      1641564.33      6941715.24      1641333.02      6942067.60
      1641267.96      6942197.72      1641247.25      6942231.73
      1641230.99      6942298.27      1641220.63      6942462.45
#Sta/Elev= 30
  4396.1 1685.94  4461.9 1685.23  4498.1 1684.34  4534.3 1683.92  4542.9 1684.21
  4600.6 1683.35  4614.7 1683.61  4715.1 1683.05  4820.6 1683.12  4894.3 1682.23
  4894.7 1681.73  4898.7 1681.73  4899.0 1682.23  4913.4 1682.66  4919.0 1682.40
  4929.8 1684.74  4941.4 1685.64  4952.2 1684.87  4979.7 1684.60  4995.1 1683.78
  5000.3 1684.47  5009.3 1684.56  5034.3 1684.06  5068.7 1684.66  5081.1 1684.25
  5091.6 1684.77  5111.2 1686.83  5131.2 1687.84  5151.3 1688.01  5235.9 1692.63
#Mann=3,-1,0
  4396.1    0.05       0  4894.3    0.05       0  4899.0    0.05       0
Bank Sta=4894.3,4899
Exp/Cntr=0.3,0.1

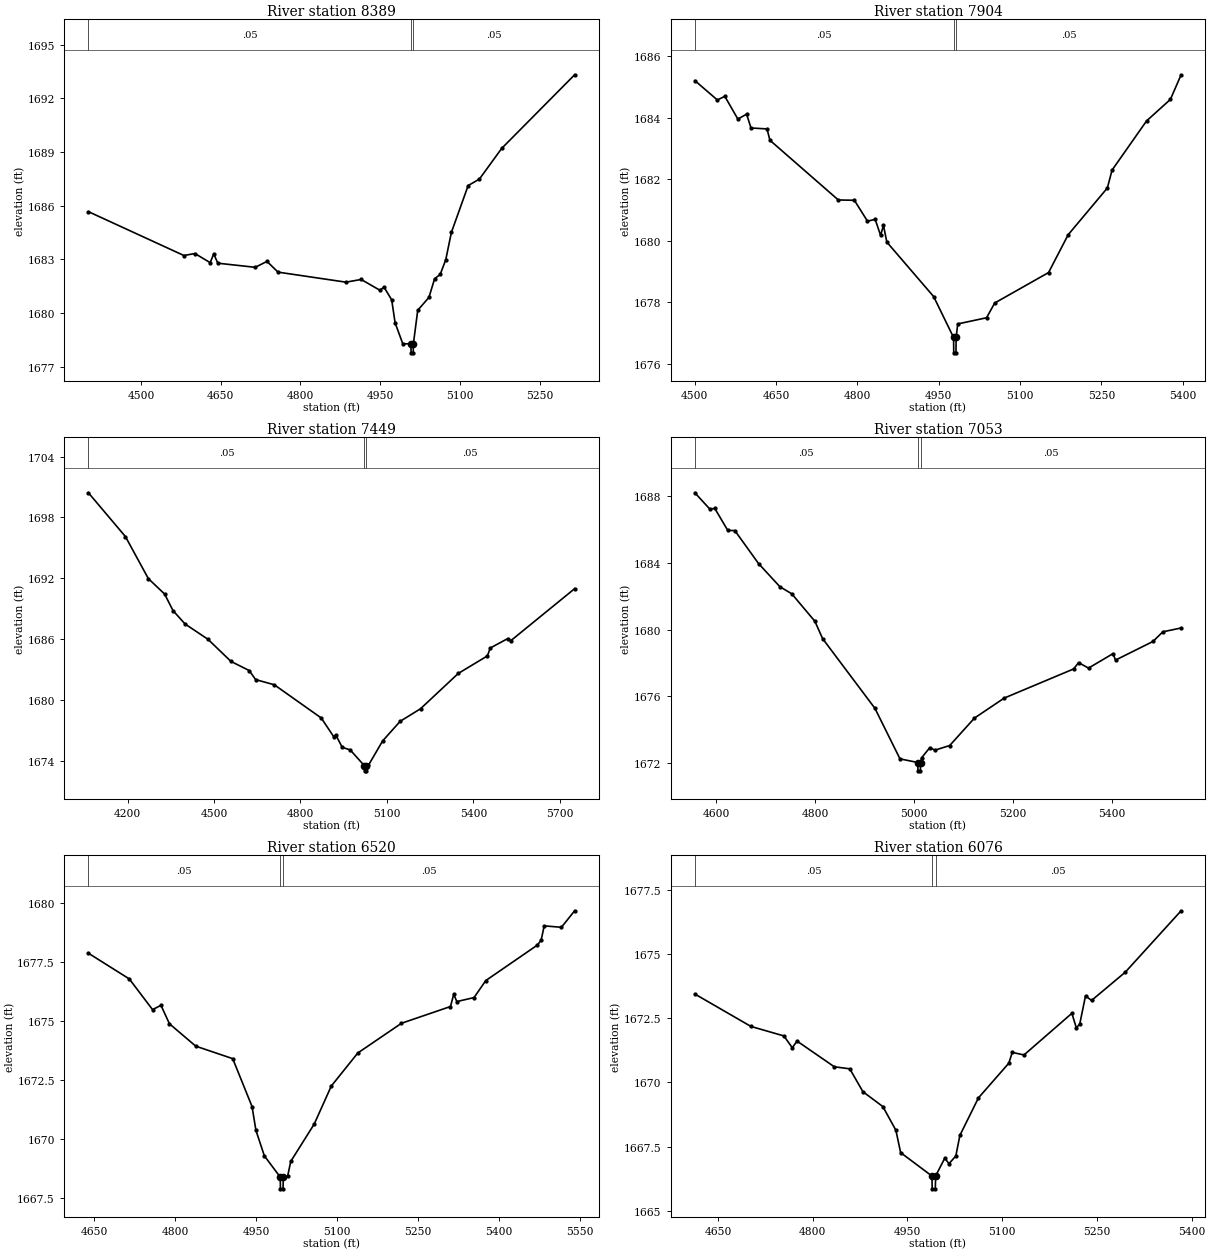
Type RM Length L Ch R = 1,8389,485,485,485
BEGIN DESCRIPTION:
Deadman 23 18.0
END DESCRIPTION:
XS GIS Cut Line= 3
      1641535.55      6941676.00      1641155.00      6942138.00
      1641054.99      6942438.02
#Sta/Elev= 30
  4401.0 1685.67  4580.6 1683.22  4601.4 1683.33  4630.1 1682.82  4636.8 1683.31
  4644.5 1682.79  4714.8 1682.56  4737.0 1682.89  4757.8 1682.29  4885.5 1681.73
  4914.2 1681.88  4949.3 1681.28  4957.2 1681.45  4971.6 1680.74  4978.0 1679.46
  4992.4 1678.29  5007.7 1678.28  5008.1 1677.78  5012.1 1677.78  5012.4 1678.28
  5020.6 1680.16  5041.7 1680.88  5052.3 1681.92  5062.8 1682.16  5073.3 1682.98
  5083.9 1684.51  5115.5 1687.13  5136.6 1687.49  5178.7 1689.21  5315.8 1693.32
#Mann=3,-1,0
  4401.0    0.05       0  5007.7    0.03       0  5012.4    0.05       0
Bank Sta=5007.7,5012.4
Exp/Cntr=0.3,0.1

Type RM Length L Ch R = 1,7904,455,455,455
BEGIN DESCRIPTION:
Deadman 23 17.0
END DESCRIPTION:
XS GIS Cut Line= 3
      1641513.49      6941503.33      1641055.00      6941688.00
      1640833.86      6942024.45
#Sta/Elev= 30
  4500.2 1685.21  4541.7 1684.58  4555.4 1684.70  4579.5 1683.96  4595.6 1684.12
  4603.7 1683.67  4633.2 1683.64  4638.7 1683.27  4764.8 1681.33  4794.4 1681.32
  4818.6 1680.64  4832.8 1680.70  4842.7 1680.18  4848.1 1680.50  4854.3 1679.96
  4940.6 1678.19  4977.4 1676.86  4977.7 1676.36  4981.8 1676.36  4982.1 1676.86
  4985.1 1677.30  5038.2 1677.50  5053.3 1677.98  5152.6 1678.97  5188.8 1680.20
  5261.1 1681.72  5269.7 1682.30  5333.4 1683.90  5377.4 1684.60  5397.1 1685.40
#Mann=3,-1,0
  4500.2    0.05       0  4977.4    0.03       0  4982.1    0.05       0
Bank Sta=4977.4,4982.1
Exp/Cntr=0.3,0.1

Type RM Length L Ch R = 1,7449,396,396,396
BEGIN DESCRIPTION:
Deadman 23 16.0
END DESCRIPTION:
XS GIS Cut Line= 3
      1641204.98      6940788.02      1640655.00      6941538.00
      1640755.01      6942288.04
#Sta/Elev= 30
  4064.3 1700.44  4192.8 1696.11  4272.3 1691.96  4328.6 1690.44  4357.9 1688.80
  4399.7 1687.48  4479.1 1685.97  4558.6 1683.79  4622.3 1682.88  4644.3 1681.99
  4709.1 1681.48  4872.0 1678.20  4916.0 1676.32  4922.2 1676.54  4944.7 1675.30
  4972.3 1675.05  5021.8 1673.48  5022.2 1672.98  5026.9 1672.98  5027.4 1673.48
  5035.9 1673.54  5085.1 1675.94  5145.7 1677.87  5216.3 1679.11  5347.4 1682.60
  5448.3 1684.33  5458.4 1685.11  5518.9 1686.04  5529.0 1685.82  5751.0 1690.97
#Mann=3,-1,0
  4064.3    0.05       0  5021.8    0.03       0  5027.4    0.05       0
Bank Sta=5021.8,5027.4
Exp/Cntr=0.3,0.1

Type RM Length L Ch R = 1,7053,533,533,533
BEGIN DESCRIPTION:
Deadman 23 15.0
END DESCRIPTION:
XS GIS Cut Line= 3
      1640380.58      6940958.22      1640311.06      6941396.14
      1640269.83      6941934.76
#Sta/Elev= 30
  4556.6 1688.22  4586.8 1687.24  4596.9 1687.28  4623.1 1685.96  4637.4 1685.95
  4685.4 1683.97  4728.5 1682.58  4752.7 1682.15  4799.4 1680.50  4815.0 1679.46
  4920.9 1675.27  4971.5 1672.24  5007.5 1672.02  5008.0 1671.52  5012.8 1671.52
  5013.2 1672.02  5015.4 1672.31  5032.0 1672.92  5042.0 1672.76  5072.1 1673.04
  5122.2 1674.69  5182.4 1675.89  5322.8 1677.64  5332.8 1678.02  5352.9 1677.69
  5402.5 1678.56  5407.5 1678.17  5483.3 1679.29  5503.3 1679.87  5540.2 1680.10
#Mann=3,-1,0
  4556.6    0.05       0  5007.5    0.03       0  5013.2    0.05       0
Bank Sta=5007.5,5013.2
Exp/Cntr=0.3,0.1

Type RM Length L Ch R = 1,6520,444,444,444
BEGIN DESCRIPTION:
Deadman 23 14.0
END DESCRIPTION:
XS GIS Cut Line= 3
      1639672.30      6941276.47      1639855.00      6941588.00
      1640119.67      6942058.52
#Sta/Elev= 30
  4639.1 1677.86  4714.9 1676.77  4757.9 1675.47  4773.6 1675.65  4789.2 1674.87
  4838.0 1673.92  4906.5 1673.39  4942.3 1671.36  4949.5 1670.35  4965.1 1669.27
  4994.5 1668.37  4995.0 1667.87  4999.8 1667.87  5000.2 1668.37  5008.2 1668.40
  5014.0 1669.03  5057.6 1670.62  5089.2 1672.23  5138.3 1673.63  5219.2 1674.89
  5310.0 1675.60  5316.1 1676.12  5321.8 1675.81  5353.7 1675.98  5375.4 1676.70
  5470.7 1678.20  5478.0 1678.41  5483.7 1679.02  5515.6 1678.96  5540.1 1679.66
#Mann=3,-1,0
  4639.1    0.05       0  4994.5    0.05       0  5000.2    0.05       0
Bank Sta=4994.5,5000.2
Exp/Cntr=0.3,0.1

Type RM Length L Ch R = 1,6076,465,465,465
BEGIN DESCRIPTION:
Deadman 23 13.0
END DESCRIPTION:
XS GIS Cut Line= 3
      1639396.85      6941472.94      1639505.00      6941838.00
      1639652.07      6942198.09
#Sta/Elev= 30
  4613.6 1673.44  4702.3 1672.18  4754.5 1671.81  4767.8 1671.35  4775.3 1671.61
  4834.3 1670.61  4858.8 1670.53  4879.6 1669.64  4911.2 1669.06  4931.8 1668.14
  4939.3 1667.27  4988.8 1666.36  4989.3 1665.86  4994.2 1665.86  4994.7 1666.36
  5009.1 1667.05  5015.9 1666.84  5026.7 1667.14  5033.1 1667.94  5062.5 1669.40
  5110.6 1670.75  5116.0 1671.17  5134.6 1671.07  5210.4 1672.69  5217.5 1672.12
  5222.9 1672.28  5232.0 1673.37  5241.5 1673.19  5294.9 1674.29  5383.3 1676.68
#Mann=3,-1,0
  4613.6    0.05       0  4988.8    0.03       0  4994.7    0.05       0
Bank Sta=4988.8,4994.7
Exp/Cntr=0.3,0.1

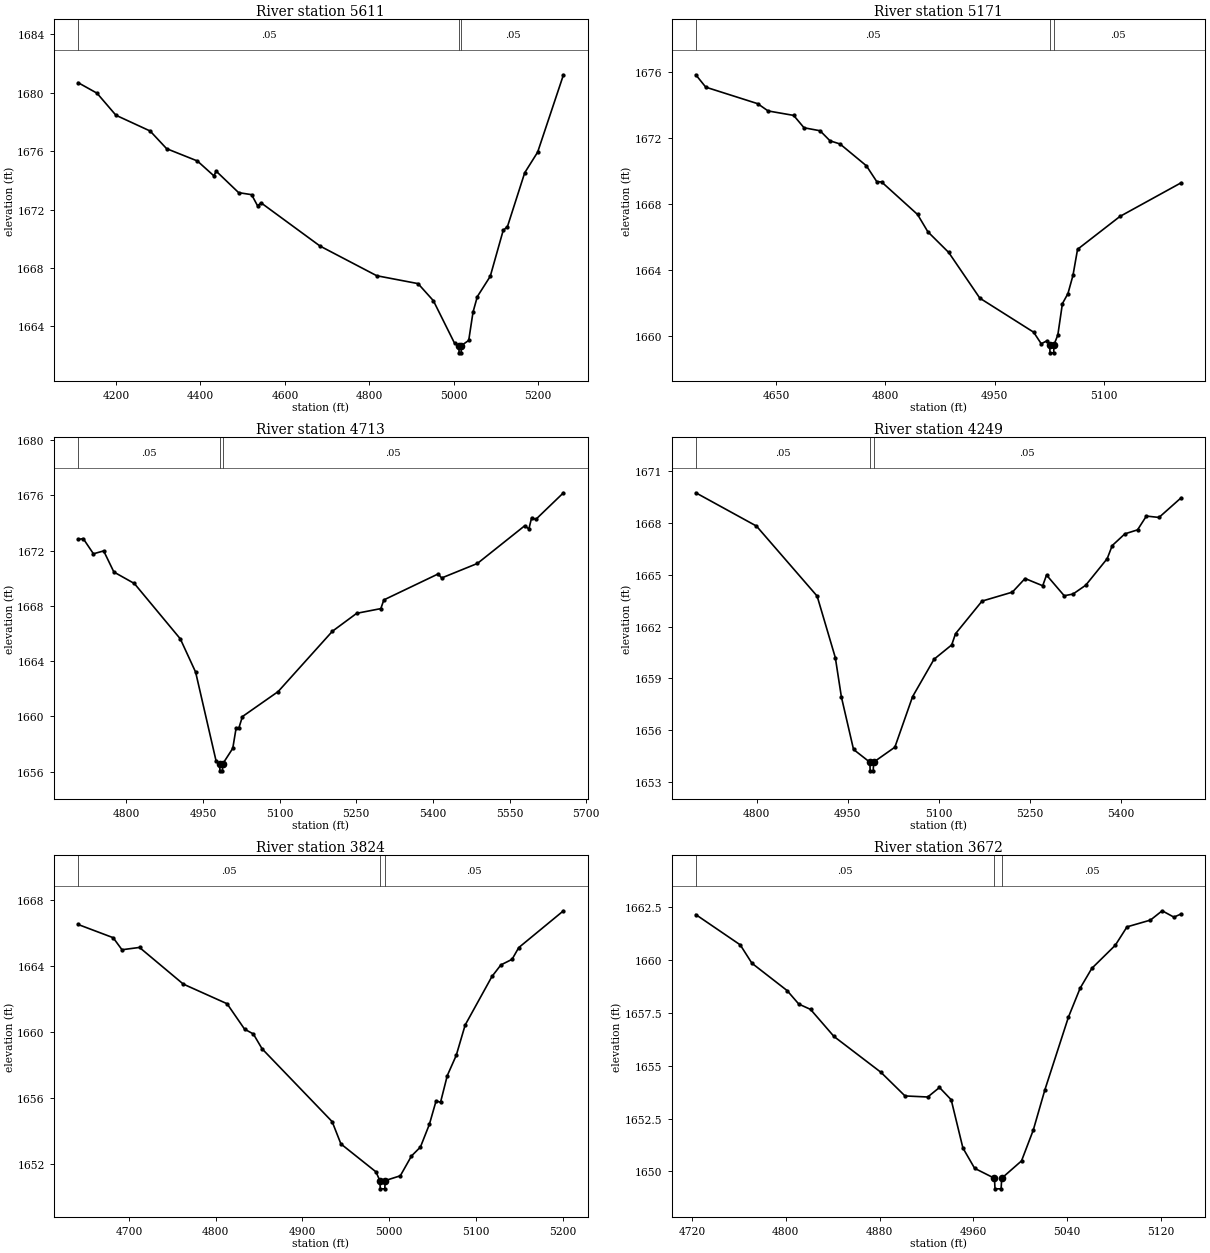
Type RM Length L Ch R = 1,5611,440,440,440
BEGIN DESCRIPTION:
Deadman 23 12.0
END DESCRIPTION:
XS GIS Cut Line= 3
      1639455.01      6941087.99      1639055.00      6941888.00
      1639005.00      6942138.01
#Sta/Elev= 30
  4110.2 1680.69  4154.9 1679.97  4199.7 1678.46  4280.7 1677.38  4319.8 1676.17
  4392.5 1675.33  4431.7 1674.31  4437.2 1674.63  4490.3 1673.16  4521.1 1673.02
  4535.1 1672.26  4543.5 1672.46  4683.2 1669.50  4817.4 1667.47  4915.2 1666.93
  4951.5 1665.76  5001.8 1662.84  5011.9 1662.69  5012.4 1662.19  5017.3 1662.19
  5017.8 1662.69  5035.2 1663.04  5045.4 1664.98  5055.6 1666.04  5086.2 1667.43
  5116.8 1670.57  5127.0 1670.84  5167.8 1674.52  5198.4 1675.93  5259.6 1681.23
#Mann=3,-1,0
  4110.2    0.05       0  5011.9    0.03       0  5017.8    0.05       0
Bank Sta=5011.9,5017.8
Exp/Cntr=0.3,0.1

Type RM Length L Ch R = 1,5171,458,458,458
BEGIN DESCRIPTION:
Deadman 23 11.0
END DESCRIPTION:
XS GIS Cut Line= 3
      1639204.98      6941238.01      1638855.00      6941538.00
      1638730.50      6941701.80
#Sta/Elev= 30
  4539.6 1675.81  4553.3 1675.06  4624.6 1674.06  4638.9 1673.62  4674.0 1673.35
  4688.3 1672.60  4710.3 1672.42  4724.0 1671.81  4737.7 1671.62  4773.9 1670.30
  4788.2 1669.34  4794.8 1669.32  4844.2 1667.35  4858.4 1666.30  4887.0 1665.05
  4929.8 1662.28  5003.7 1660.22  5014.1 1659.52  5022.4 1659.71  5025.7 1659.47
  5026.2 1658.97  5031.2 1658.97  5031.7 1659.47  5036.9 1660.05  5043.2 1661.95
  5050.8 1662.56  5057.7 1663.66  5064.0 1665.24  5122.2 1667.23  5206.3 1669.27
#Mann=3,-1,0
  4539.6    0.05       0  5025.7    0.03       0  5031.7    0.05       0
Bank Sta=5025.7,5031.7
Exp/Cntr=0.3,0.1

Type RM Length L Ch R = 1,4713,464,464,464
BEGIN DESCRIPTION:
Deadman 23 10.0
END DESCRIPTION:
XS GIS Cut Line= 3
      1638505.00      6941038.04      1638505.00      6941338.00
      1638755.01      6941938.03
#Sta/Elev= 30
  4705.6 1672.81  4715.6 1672.87  4735.6 1671.77  4755.6 1671.98  4775.6 1670.45
  4815.6 1669.62  4905.6 1665.61  4935.6 1663.20  4975.6 1656.77  4982.6 1656.55
  4983.1 1656.05  4988.1 1656.05  4988.6 1656.55  5008.3 1657.68  5014.8 1659.14
  5020.2 1659.15  5027.2 1659.98  5097.1 1661.79  5203.3 1666.16  5250.9 1667.46
  5298.1 1667.80  5304.0 1668.43  5410.2 1670.31  5417.2 1670.02  5487.1 1671.07
  5579.7 1673.80  5587.9 1673.57  5593.3 1674.39  5601.4 1674.26  5655.6 1676.19
#Mann=3,-1,0
  4705.6    0.05       0  4982.6    0.05       0  4988.6    0.05       0
Bank Sta=4982.6,4988.6
Exp/Cntr=0.3,0.1

Type RM Length L Ch R = 1,4249,425,425,425
BEGIN DESCRIPTION:
Deadman 23 9.0
END DESCRIPTION:
XS GIS Cut Line= 3
      1638105.00      6941138.03      1638105.00      6941438.00
      1638405.02      6941838.03
#Sta/Elev= 30
  4699.6 1669.76  4799.6 1667.83  4899.6 1663.77  4929.6 1660.20  4939.6 1657.92
  4959.6 1654.88  4986.5 1654.14  4987.0 1653.64  4992.1 1653.64  4992.6 1654.14
  5027.7 1655.01  5056.9 1657.94  5092.3 1660.11  5121.4 1660.94  5127.7 1661.59
  5171.4 1663.48  5221.4 1664.00  5242.3 1664.79  5271.4 1664.37  5277.7 1664.99
  5306.9 1663.79  5321.4 1663.89  5342.3 1664.40  5377.7 1665.94  5386.0 1666.70
  5406.9 1667.38  5427.7 1667.61  5442.3 1668.41  5463.1 1668.33  5499.6 1669.47
#Mann=3,-1,0
  4699.6    0.05       0  4986.5    0.03       0  4992.6    0.05       0
Bank Sta=4986.5,4992.6
Exp/Cntr=0.3,0.1

Type RM Length L Ch R = 1,3824,152,152,152
BEGIN DESCRIPTION:
Deadman 23 8.0
END DESCRIPTION:
XS GIS Cut Line= 3
      1637805.01      6941287.96      1637755.00      6941638.00
      1637805.01      6941838.05
#Sta/Elev= 30
  4641.3 1666.49  4681.7 1665.69  4691.9 1664.96  4712.1 1665.10  4762.6 1662.88
  4813.1 1661.69  4833.3 1660.15  4843.4 1659.86  4853.5 1658.96  4934.3 1654.55
  4944.4 1653.20  4984.8 1651.51  4989.3 1650.98  4989.8 1650.48  4995.0 1650.48
  4995.5 1650.98  5012.9 1651.27  5025.8 1652.47  5036.1 1653.01  5046.4 1654.38
  5054.2 1655.81  5059.3 1655.72  5067.1 1657.34  5077.4 1658.56  5087.7 1660.40
  5118.6 1663.34  5128.9 1664.04  5141.8 1664.38  5149.5 1665.09  5201.1 1667.32
#Mann=3,-1,0
  4641.3    0.05       0  4989.3    0.05       0  4995.5    0.05       0
Bank Sta=4989.3,4995.5
Exp/Cntr=0.3,0.1

Type RM Length L Ch R = 1,3672,294,294,294
BEGIN DESCRIPTION:
Mapping XS 30c11b35
END DESCRIPTION:
XS GIS Cut Line= 2
      1637622.55      6941410.13      1637616.49      6941824.18
#Sta/Elev= 30
  4723.2 1662.14  4761.1 1660.71  4771.1 1659.84  4801.1 1658.55  4811.1 1657.91
  4821.1 1657.66  4841.1 1656.38  4881.1 1654.69  4901.7 1653.57  4921.1 1653.52
  4931.1 1653.97  4941.1 1653.39  4951.1 1651.11  4961.1 1650.15  4978.0 1649.68
  4978.5 1649.18  4983.7 1649.18  4984.2 1649.68  5001.1 1650.50  5011.1 1651.95
  5021.1 1653.87  5041.1 1657.29  5051.1 1658.66  5061.1 1659.60  5081.1 1660.69
  5091.1 1661.56  5111.1 1661.88  5121.1 1662.32  5131.1 1662.02  5137.3 1662.17
#Mann=3,-1,0
  4723.2    0.05       0  4978.0    0.05       0  4984.2    0.05       0
Bank Sta=4978,4984.2
Exp/Cntr=0.3,0.1

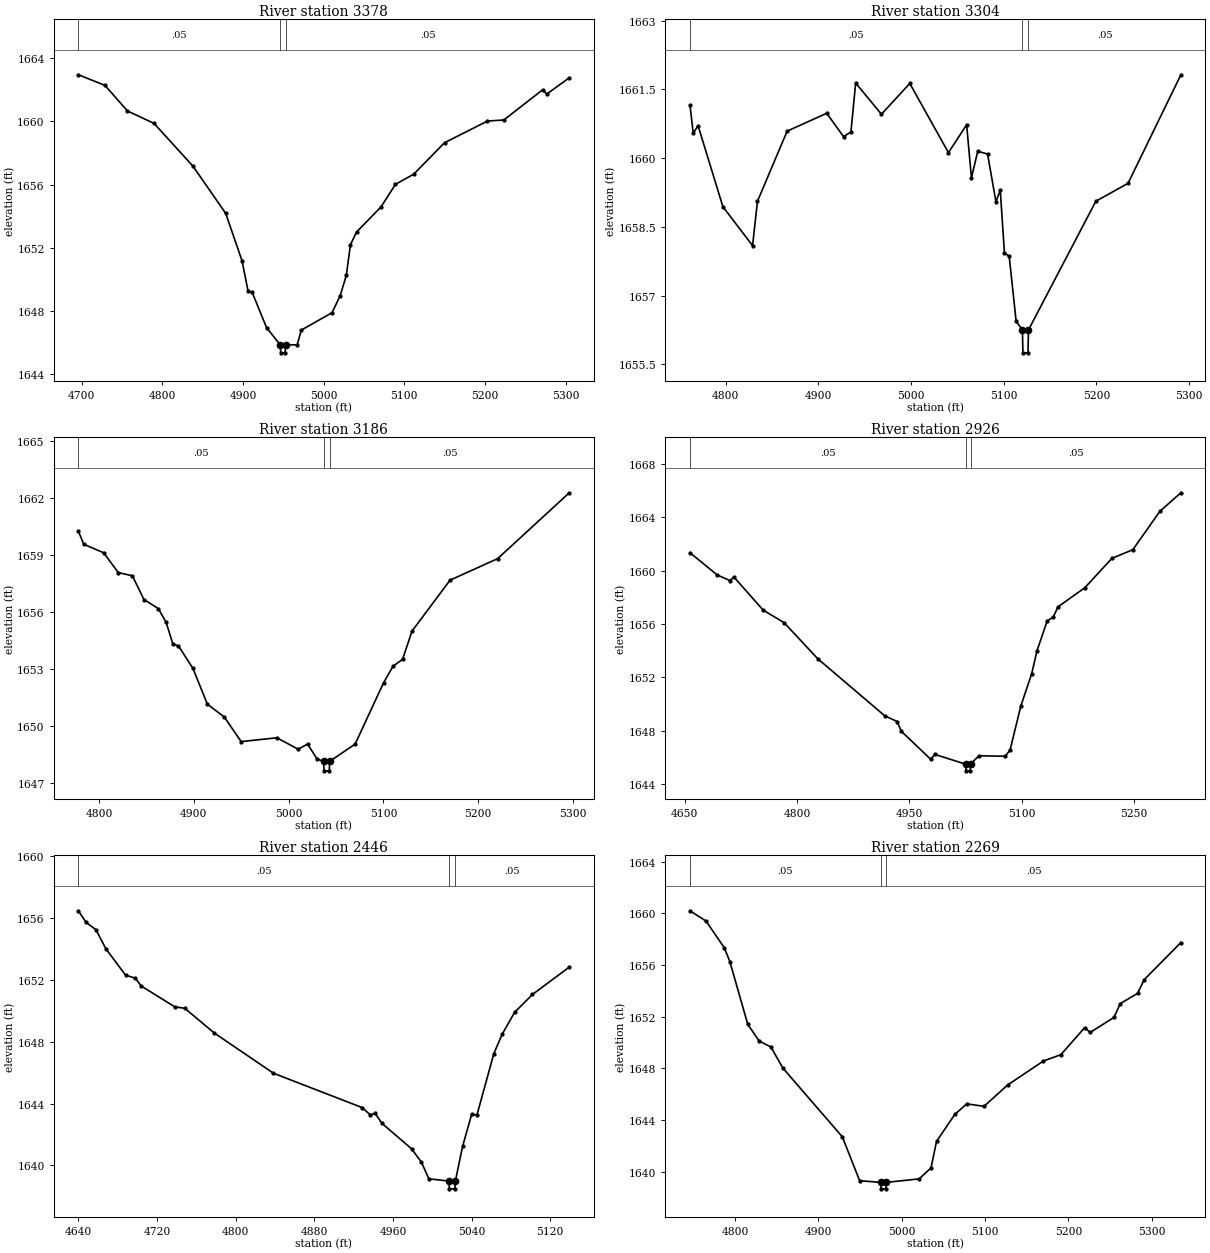
Type RM Length L Ch R = 1,3378,74,74,74
BEGIN DESCRIPTION:
Deadman 23 7.0
END DESCRIPTION:
XS GIS Cut Line= 3
      1637405.00      6941338.02      1637355.00      6941638.00
      1637304.99      6941938.04
#Sta/Elev= 30
  4696.1 1662.95  4729.0 1662.28  4756.9 1660.66  4789.9 1659.87  4838.0 1657.17
  4878.6 1654.18  4898.8 1651.19  4906.4 1649.25  4911.5 1649.17  4929.3 1646.94
  4946.3 1645.85  4946.8 1645.35  4952.3 1645.35  4952.8 1645.85  4967.3 1645.86
  4972.3 1646.79  5010.4 1647.89  5020.5 1648.97  5028.1 1650.25  5033.2 1652.19
  5040.8 1653.00  5071.2 1654.59  5088.9 1656.01  5111.7 1656.66  5149.8 1658.65
  5203.0 1660.02  5223.3 1660.09  5271.4 1662.00  5276.5 1661.73  5304.4 1662.76
#Mann=3,-1,0
  4696.1    0.05       0  4946.3    0.05       0  4952.8    0.05       0
Bank Sta=4946.3,4952.8
Exp/Cntr=0.3,0.1

Type RM Length L Ch R = 1,3304,118,118,118
BEGIN DESCRIPTION:
Mapping XS a1831d34
END DESCRIPTION:
XS GIS Cut Line= 5
      1637351.14      6941389.90      1637306.57      6941527.65
      1637284.29      6941632.97      1637310.63      6941711.96
      1637290.55      6941904.72
#Sta/Elev= 30
  4761.6 1661.16  4765.1 1660.54  4770.3 1660.71  4797.1 1658.94  4829.1 1658.09
  4834.4 1659.06  4866.4 1660.59  4909.1 1660.98  4927.2 1660.47  4935.2 1660.57
  4940.3 1661.64  4968.1 1660.96  4998.7 1661.63  5040.4 1660.12  5060.0 1660.73
  5065.2 1659.57  5072.0 1660.15  5082.6 1660.09  5091.6 1659.05  5096.3 1659.30
  5100.8 1657.93  5105.9 1657.86  5113.4 1656.44  5120.2 1656.25  5120.7 1655.75
  5126.2 1655.75  5126.7 1656.25  5199.4 1659.06  5234.1 1659.45  5291.1 1661.82
#Mann=3,-1,0
  4761.6    0.05       0  5120.2    0.05       0  5126.7    0.05       0
Bank Sta=5120.2,5126.7
Exp/Cntr=0.3,0.1

Type RM Length L Ch R = 1,3186,260,260,260
BEGIN DESCRIPTION:
Mapping XS c30c341c
END DESCRIPTION:
XS GIS Cut Line= 3
      1637264.02      6941389.95      1637183.02      6941517.52
      1637164.82      6941883.55
#Sta/Elev= 30
  4778.4 1660.26  4784.0 1659.57  4805.1 1659.12  4820.4 1658.08  4835.3 1657.91
  4847.5 1656.66  4862.7 1656.18  4870.9 1655.46  4878.0 1654.32  4883.9 1654.22
  4899.2 1653.03  4914.4 1651.15  4932.3 1650.47  4950.0 1649.18  4987.7 1649.38
  5010.1 1648.78  5020.1 1649.05  5030.1 1648.26  5036.9 1648.14  5037.4 1647.64
  5042.9 1647.64  5043.4 1648.14  5070.2 1649.05  5100.2 1652.28  5110.2 1653.15
  5120.2 1653.51  5130.2 1655.00  5170.3 1657.68  5220.4 1658.81  5296.0 1662.28
#Mann=3,-1,0
  4778.4    0.05       0  5036.9    0.05       0  5043.4    0.05       0
Bank Sta=5036.9,5043.4
Exp/Cntr=0.3,0.1

Type RM Length L Ch R = 1,2926,480,480,480
BEGIN DESCRIPTION:
Deadman 23 6.0
END DESCRIPTION:
XS GIS Cut Line= 3
      1637254.99      6941338.00      1636955.00      6941488.00
      1636704.97      6941688.03
#Sta/Elev= 30
  4657.2 1661.34  4693.5 1659.68  4710.3 1659.26  4715.9 1659.52  4755.0 1657.04
  4783.0 1656.10  4827.7 1653.41  4917.1 1649.14  4933.9 1648.70  4939.5 1647.97
  4978.6 1645.88  4984.2 1646.24  5025.4 1645.51  5025.9 1645.01  5031.4 1645.01
  5031.9 1645.51  5043.0 1646.14  5078.2 1646.10  5084.6 1646.56  5099.1 1649.87
  5113.5 1652.27  5120.7 1654.01  5134.3 1656.24  5142.3 1656.52  5148.7 1657.29
  5184.7 1658.73  5220.7 1660.92  5248.7 1661.57  5284.7 1664.44  5312.8 1665.83
#Mann=3,-1,0
  4657.2    0.05       0  5025.4    0.03       0  5031.9    0.05       0
Bank Sta=5025.4,5031.9
Exp/Cntr=0.3,0.1

Type RM Length L Ch R = 1,2446,177,177,177
BEGIN DESCRIPTION:
Deadman 23 5.0
END DESCRIPTION:
XS GIS Cut Line= 3
      1637162.78      6941118.50      1636805.00      6941088.00
      1636672.57      6941134.72
#Sta/Elev= 30
  4639.9 1656.46  4647.7 1655.71  4657.7 1655.24  4667.8 1654.01  4687.9 1652.30
  4697.9 1652.10  4703.8 1651.60  4738.0 1650.25  4748.1 1650.16  4778.2 1648.56
  4838.4 1645.96  4928.7 1643.74  4936.9 1643.27  4941.9 1643.36  4948.8 1642.72
  4978.9 1641.08  4988.9 1640.22  4996.5 1639.14  5016.9 1638.99  5017.4 1638.49
  5023.0 1638.49  5023.5 1638.99  5030.8 1641.23  5040.1 1643.31  5045.4 1643.25
  5062.6 1647.22  5071.0 1648.47  5083.8 1649.90  5101.9 1651.05  5139.4 1652.82
#Mann=3,-1,0
  4639.9    0.05       0  5016.9    0.03       0  5023.5    0.05       0
Bank Sta=5016.9,5023.5
Exp/Cntr=0.3,0.1

Type RM Length L Ch R = 1,2269,305,305,305
BEGIN DESCRIPTION:
Mapping XS 657c3130
END DESCRIPTION:
XS GIS Cut Line= 2
      1636950.11      6940725.55      1636565.25      6941171.17
#Sta/Elev= 30
  4746.0 1660.19  4765.3 1659.39  4787.2 1657.32  4793.8 1656.26  4815.3 1651.40
  4828.9 1650.11  4843.1 1649.64  4857.4 1648.01  4928.7 1642.69  4949.5 1639.29
  4974.7 1639.16  4975.2 1638.66  4980.9 1638.66  4981.4 1639.16  5020.8 1639.43
  5035.1 1640.28  5041.7 1642.33  5063.6 1644.42  5077.9 1645.24  5098.7 1645.05
  5127.2 1646.71  5170.0 1648.56  5190.9 1649.05  5219.4 1651.14  5226.0 1650.77
  5254.5 1651.93  5262.1 1653.00  5283.0 1653.80  5290.7 1654.85  5334.8 1657.73
#Mann=3,-1,0
  4746.0    0.05       0  4974.7    0.03       0  4981.4    0.05       0
Bank Sta=4974.7,4981.4
Exp/Cntr=0.3,0.1