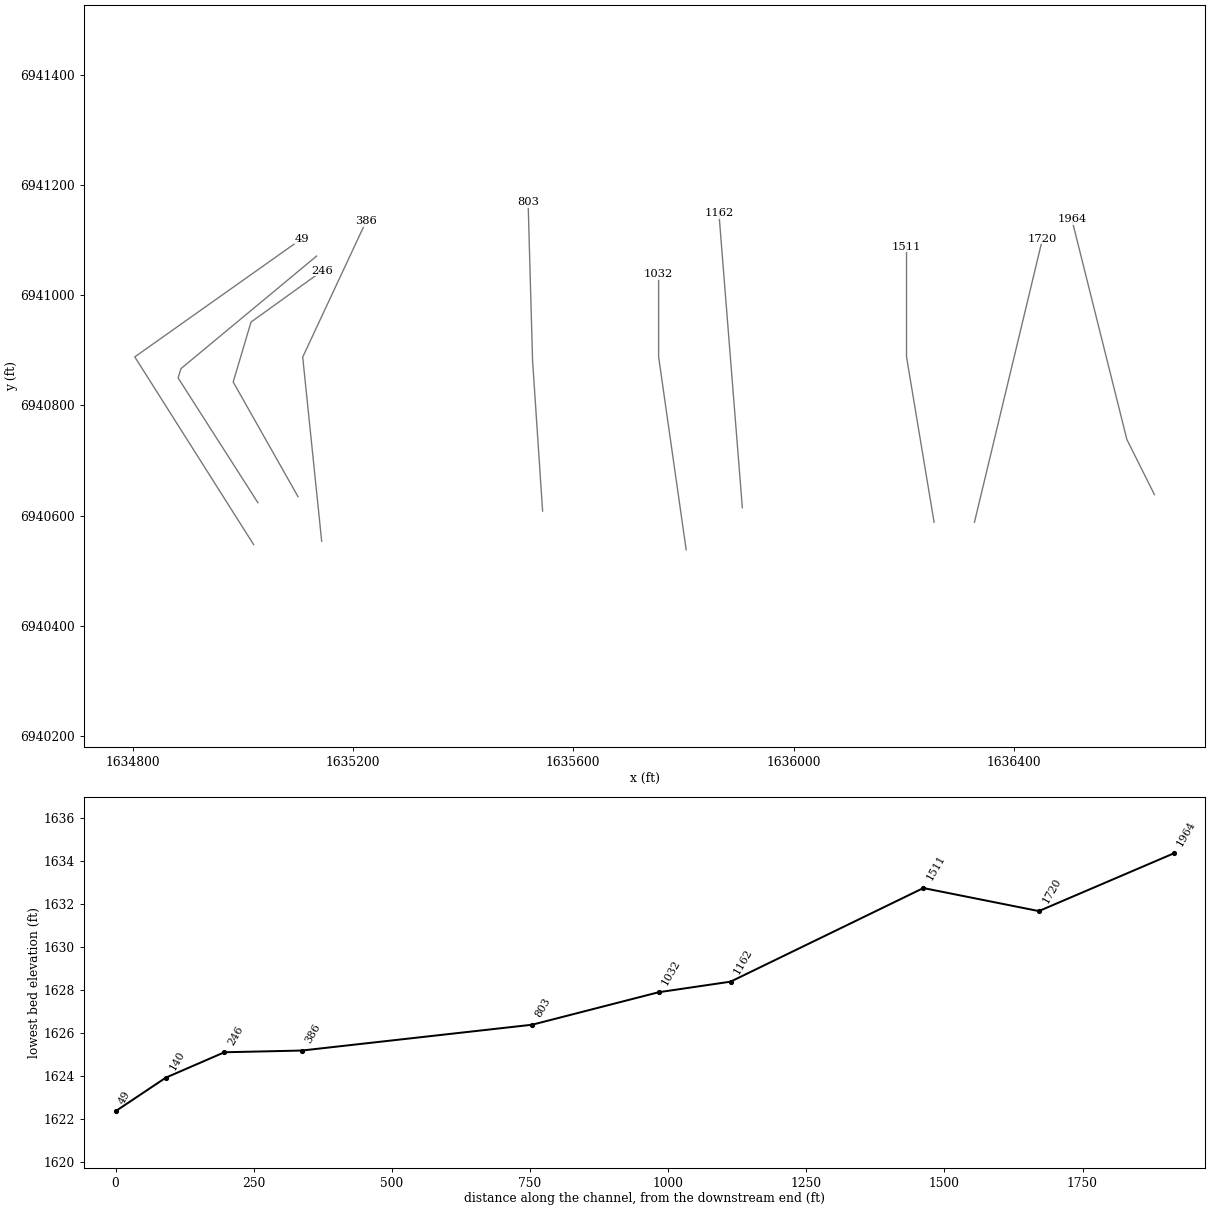
HEC-RAS study Deadman 23.prj: Deadman 23 Base Level Engineering

--- Deadman 23.g01 (geometry) --- (continued)

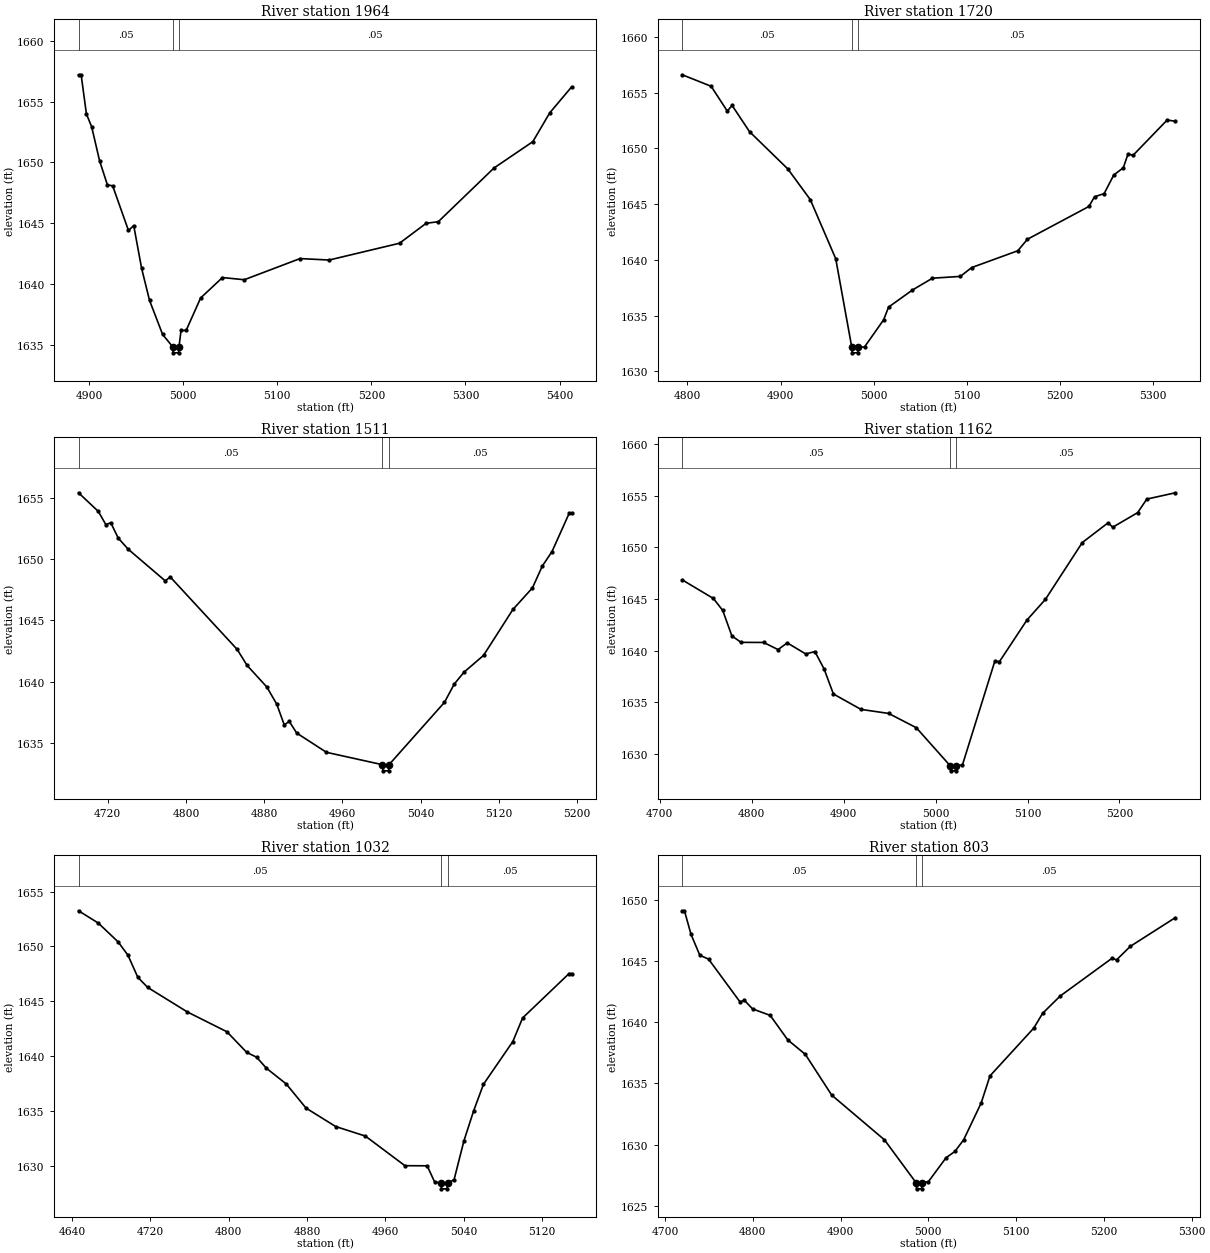
Type RM Length L Ch R = 1,1964,244,244,244
BEGIN DESCRIPTION:
Deadman 23 4.0
END DESCRIPTION:
XS GIS Cut Line= 3
      1636655.00      6940638.00      1636605.00      6940738.00
      1636505.00      6941137.98
#Sta/Elev= 30
  4888.7 1657.21  4891.5 1657.21  4897.1 1653.99  4902.7 1652.93  4911.1 1650.14
  4919.4 1648.16  4925.0 1648.08  4941.8 1644.41  4947.4 1644.81  4955.8 1641.29
  4964.2 1638.66  4978.1 1635.86  4988.8 1634.85  4989.3 1634.35  4995.0 1634.35
  4995.5 1634.85  4997.7 1636.19  5003.1 1636.19  5018.5 1638.86  5041.7 1640.54
  5064.9 1640.36  5124.2 1642.10  5155.1 1641.98  5229.9 1643.36  5258.2 1645.00
  5271.1 1645.13  5330.4 1649.55  5371.6 1651.71  5389.6 1654.08  5412.8 1656.21
#Mann=3,-1,0
  4888.7    0.05       0  4988.8    0.05       0  4995.5    0.05       0
Bank Sta=4988.8,4995.5
Exp/Cntr=0.3,0.1

Type RM Length L Ch R = 1,1720,209,209,209
BEGIN DESCRIPTION:
Mapping XS 39741223
END DESCRIPTION:
XS GIS Cut Line= 2
      1636328.28      6940587.83      1636451.83      6941102.30
#Sta/Elev= 30
  4794.5 1656.59  4825.5 1655.56  4842.8 1653.34  4848.0 1653.84  4866.7 1651.49
  4907.8 1648.15  4931.9 1645.40  4959.2 1640.10  4976.4 1632.17  4976.9 1631.67
  4982.6 1631.67  4983.1 1632.17  4990.1 1632.20  5010.6 1634.63  5015.9 1635.77
  5041.5 1637.30  5063.0 1638.36  5092.9 1638.52  5105.0 1639.31  5154.6 1640.82
  5164.9 1641.85  5230.9 1644.79  5236.9 1645.66  5247.2 1645.94  5257.5 1647.60
  5267.8 1648.26  5272.9 1649.51  5278.1 1649.36  5314.9 1652.54  5323.6 1652.42
#Mann=3,-1,0
  4794.5    0.05       0  4976.4    0.05       0  4983.1    0.05       0
Bank Sta=4976.4,4983.1
Exp/Cntr=0.3,0.1

Type RM Length L Ch R = 1,1511,349,349,349
BEGIN DESCRIPTION:
Deadman 23 3.0
END DESCRIPTION:
XS GIS Cut Line= 3
      1636255.00      6940587.98      1636205.00      6940888.00
      1636205.00      6941088.04
#Sta/Elev= 30
  4690.2 1655.40  4710.5 1653.88  4718.1 1652.81  4723.2 1652.96  4730.8 1651.71
  4740.9 1650.81  4778.9 1648.22  4784.0 1648.54  4852.4 1642.64  4862.6 1641.33
  4882.8 1639.57  4893.0 1638.16  4900.6 1636.48  4905.7 1636.77  4913.3 1635.82
  4943.7 1634.25  5001.0 1633.24  5001.5 1632.74  5007.2 1632.74  5007.7 1633.24
  5064.4 1638.32  5074.4 1639.81  5084.4 1640.78  5104.4 1642.15  5134.4 1645.89
  5154.4 1647.65  5164.4 1649.42  5174.4 1650.61  5191.9 1653.72  5194.4 1653.72
#Mann=3,-1,0
  4690.2    0.05       0  5001.0    0.05       0  5007.7    0.05       0
Bank Sta=5001,5007.7
Exp/Cntr=0.3,0.1

Type RM Length L Ch R = 1,1162,130,130,130
BEGIN DESCRIPTION:
Mapping XS 9a632369
END DESCRIPTION:
XS GIS Cut Line= 2
      1635906.98      6940614.17      1635864.45      6941148.88
#Sta/Elev= 30
  4724.4 1646.85  4758.3 1645.05  4768.4 1643.90  4778.4 1641.43  4788.4 1640.81
  4813.0 1640.80  4828.6 1640.11  4838.6 1640.76  4858.7 1639.69  4868.7 1639.92
  4878.7 1638.24  4888.8 1635.82  4918.8 1634.33  4948.9 1633.94  4979.0 1632.56
  5015.8 1628.89  5016.3 1628.39  5022.0 1628.39  5022.5 1628.89  5029.2 1628.96
  5064.5 1639.01  5069.5 1638.95  5099.4 1642.97  5119.5 1644.97  5159.6 1650.46
  5187.7 1652.37  5192.7 1651.94  5219.8 1653.35  5229.8 1654.66  5260.8 1655.27
#Mann=3,-1,0
  4724.4    0.05       0  5015.8    0.05       0  5022.5    0.05       0
Bank Sta=5015.8,5022.5
Exp/Cntr=0.3,0.1

Type RM Length L Ch R = 1,1032,229,229,229
BEGIN DESCRIPTION:
Deadman 23 2.0
END DESCRIPTION:
XS GIS Cut Line= 3
      1635805.00      6940537.97      1635755.00      6940888.00
      1635755.00      6941038.02
#Sta/Elev= 30
  4646.6 1653.25  4666.8 1652.13  4687.0 1650.42  4697.1 1649.20  4707.2 1647.18
  4717.3 1646.26  4757.7 1644.03  4798.2 1642.22  4818.4 1640.34  4828.5 1639.90
  4838.6 1638.89  4858.8 1637.46  4879.0 1635.26  4909.3 1633.58  4939.6 1632.71
  4980.0 1630.01  5002.7 1630.00  5010.2 1628.55  5016.8 1628.40  5017.3 1627.90
  5023.0 1627.90  5023.5 1628.40  5030.2 1628.74  5040.2 1632.26  5050.2 1635.02
  5060.2 1637.43  5090.2 1641.33  5100.2 1643.48  5147.7 1647.53  5150.2 1647.53
#Mann=3,-1,0
  4646.6    0.05       0  5016.8    0.05       0  5023.5    0.05       0
Bank Sta=5016.8,5023.5
Exp/Cntr=0.3,0.1

Type RM Length L Ch R = 1,803,417,417,417
BEGIN DESCRIPTION:
Mapping XS 598a8928
END DESCRIPTION:
XS GIS Cut Line= 3
      1635544.42      6940608.06      1635526.19      6940881.52
      1635518.09      6941169.14
#Sta/Elev= 30
  4719.6 1649.09  4722.1 1649.09  4729.6 1647.16  4739.6 1645.46  4749.6 1645.14
  4785.4 1641.65  4790.4 1641.78  4799.7 1641.08  4819.8 1640.55  4839.8 1638.55
  4859.8 1637.37  4889.9 1634.04  4950.0 1630.39  4986.0 1626.89  4986.5 1626.39
  4992.3 1626.39  4992.8 1626.89  5000.1 1626.98  5020.2 1628.93  5030.2 1629.44
  5040.2 1630.39  5060.2 1633.40  5070.2 1635.61  5120.2 1639.52  5130.2 1640.72
  5150.2 1642.13  5209.4 1645.22  5214.4 1645.08  5230.2 1646.19  5281.4 1648.53
#Mann=3,-1,0
  4719.6    0.05       0  4986.0    0.05       0  4992.8    0.05       0
Bank Sta=4986,4992.8
Exp/Cntr=0.3,0.1

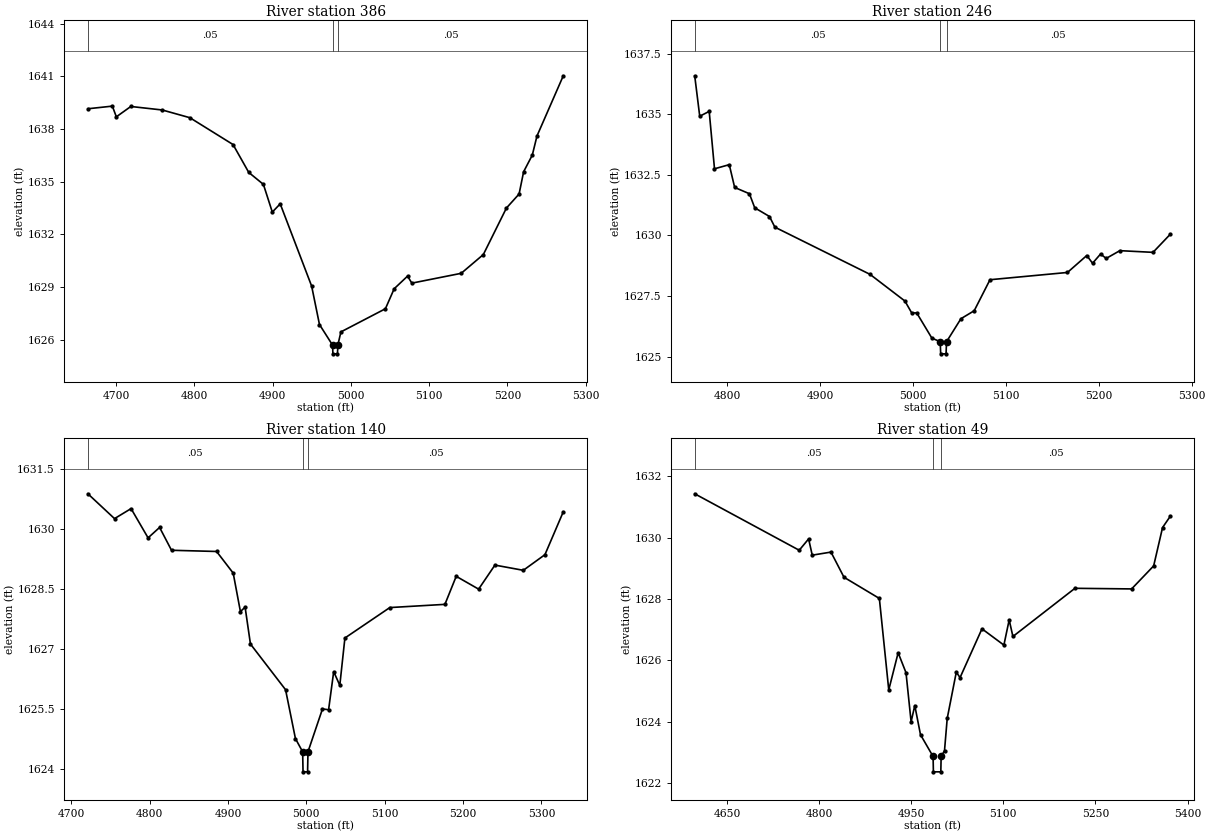
Type RM Length L Ch R = 1,386,140,140,140
BEGIN DESCRIPTION:
Mapping XS 85520c13
END DESCRIPTION:
XS GIS Cut Line= 3
      1635143.38      6940553.42      1635108.95      6940887.60
      1635224.02      6941133.90
#Sta/Elev= 30
  4663.7 1639.16  4695.0 1639.31  4700.1 1638.70  4718.6 1639.29  4758.8 1639.09
  4794.1 1638.65  4849.3 1637.12  4869.4 1635.53  4888.1 1634.85  4899.5 1633.27
  4909.6 1633.74  4949.8 1629.05  4959.8 1626.86  4976.5 1625.69  4977.0 1625.19
  4982.8 1625.19  4983.3 1625.69  4987.2 1626.44  5044.1 1627.76  5055.3 1628.90
  5072.4 1629.62  5077.9 1629.22  5141.0 1629.78  5169.3 1630.85  5198.8 1633.50
  5215.0 1634.30  5220.8 1635.57  5231.9 1636.52  5237.9 1637.61  5271.5 1641.04
#Mann=3,-1,0
  4663.7    0.05       0  4976.5    0.03       0  4983.3    0.05       0
Bank Sta=4976.5,4983.3
Exp/Cntr=0.3,0.1

Type RM Length L Ch R = 1,246,106,106,106
BEGIN DESCRIPTION:
Mapping XS fbbba91f
END DESCRIPTION:
XS GIS Cut Line= 4
      1635100.42      6940634.31      1634982.78      6940842.39
      1635015.13      6940951.20      1635144.42      6941044.17
#Sta/Elev= 30
  4765.0 1636.59  4770.4 1634.92  4780.6 1635.12  4786.3 1632.75  4802.2 1632.92
  4808.0 1631.98  4823.9 1631.72  4829.6 1631.14  4845.5 1630.78  4851.3 1630.34
  4953.8 1628.39  4991.3 1627.29  4998.6 1626.80  5004.0 1626.80  5020.3 1625.76
  5029.3 1625.61  5029.8 1625.11  5035.6 1625.11  5036.1 1625.61  5051.6 1626.56
  5065.9 1626.89  5082.9 1628.17  5166.3 1628.47  5187.1 1629.17  5193.3 1628.85
  5201.9 1629.23  5208.0 1629.05  5222.7 1629.37  5258.4 1629.30  5276.8 1630.04
#Mann=3,-1,0
  4765.0    0.05       0  5029.3    0.03       0  5036.1    0.05       0
Bank Sta=5029.3,5036.1
Exp/Cntr=0.3,0.1

Type RM Length L Ch R = 1,140,91,91,91
BEGIN DESCRIPTION:
Mapping XS f5ce0427
END DESCRIPTION:
XS GIS Cut Line= 4
      1635027.61      6940623.31      1634882.79      6940849.74
      1634887.93      6940866.65      1635134.22      6941071.03
#Sta/Elev= 30
  4721.3 1630.87  4755.3 1630.25  4776.4 1630.50  4798.1 1629.77  4812.8 1630.03
  4828.0 1629.46  4885.5 1629.43  4906.7 1628.89  4915.9 1627.93  4921.9 1628.04
  4928.7 1627.12  4973.5 1625.98  4986.1 1624.76  4995.3 1624.43  4995.8 1623.93
  5001.6 1623.93  5002.1 1624.43  5020.6 1625.50  5028.4 1625.48  5034.9 1626.43
  5042.7 1626.09  5049.2 1627.27  5106.5 1628.03  5176.8 1628.11  5191.2 1628.81
  5219.8 1628.49  5240.6 1629.09  5276.8 1628.96  5304.4 1629.35  5327.8 1630.42
#Mann=3,-1,0
  4721.3    0.05       0  4995.3    0.05       0  5002.1    0.05       0
Bank Sta=4995.3,5002.1
Exp/Cntr=0.3,0.1

Type RM Length L Ch R = 1,49,0,0,0
BEGIN DESCRIPTION:
Deadman 23 1.0
END DESCRIPTION:
XS GIS Cut Line= 3
      1635019.85      6940547.29      1634804.12      6940887.97
      1635106.91      6941102.29
#Sta/Elev= 30
  4597.4 1631.43  4767.6 1629.59  4782.9 1629.96  4788.8 1629.43  4819.3 1629.53
  4840.5 1628.71  4898.1 1628.02  4913.4 1625.04  4928.7 1626.25  4941.5 1625.60
  4949.8 1624.00  4955.8 1624.53  4965.1 1623.58  4985.6 1622.87  4986.1 1622.37
  4998.2 1622.37  4998.7 1622.87  5004.2 1623.06  5008.6 1624.11  5023.4 1625.62
  5029.5 1625.44  5065.2 1627.03  5100.9 1626.50  5109.5 1627.32  5115.6 1626.78
  5216.6 1628.35  5308.9 1628.33  5344.8 1629.08  5359.3 1630.33  5371.6 1630.69
#Mann=3,-1,0
  4597.4    0.05       0  4985.6    0.05       0  4998.7    0.05       0
Bank Sta=4985.6,4998.7
Exp/Cntr=0.3,0.1

Chan Stop Cuts=-1