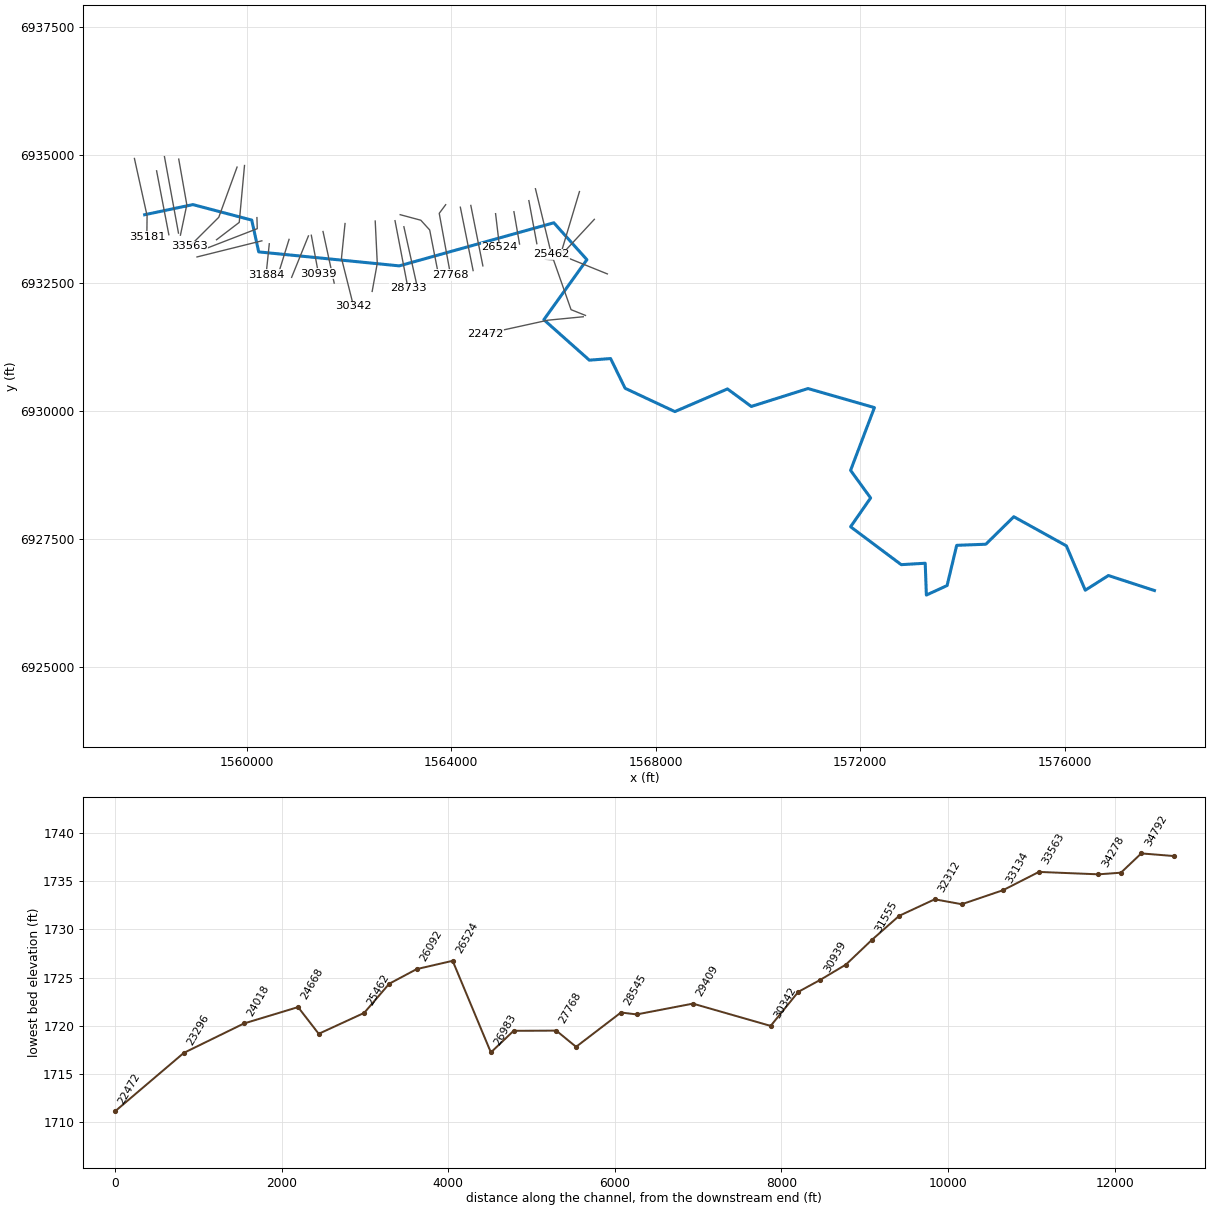
--- Deadman 24.prj (project) ---

Proj Title=Deadman 24 Base Level Engineering
Current Plan=p01
Default Exp/Contr=0.3,0.1
English Units
Geom File=g01
Flow File=f01
Plan File=p01
BEGIN DESCRIPTION:
Deadman 24
END DESCRIPTION:

--- Deadman 24.p01 (plan) ---

Plan Title=Multiple Run
Short Identifier=Multiple
Geom File=g01
Flow File=f01
Subcritical Flow
K Sum by GR= 0
Std Step Tol= 0.01
Critical Tol= 0.01
Num of Std Step Trials= 20
Max Error Tol= 0.3
Flow Tol Ratio= 0.001
Split Flow NTrial= 30
Split Flow Tol= 0.02
Split Flow Ratio= 0.02
Log Output Level= 0
Friction Slope Method= 1
Unsteady Friction Slope Method= 2
Unsteady Bridges Friction Slope Method= 1
Parabolic Critical Depth
Global Vel Dist=  1 , 1 , 1
Global Log Level= 0
CheckData=True
Encroach Param= -1, 0, 0, 0
BEGIN DESCRIPTION:
Multiple Run
END DESCRIPTION:

--- Deadman 24.f01 (steady flow) ---

Flow Title=Multiple
Number of Profiles=7
Profile Names=10-year,25-year,50-year,1pct_min,100-year,1pct_plu,500-year
River Rch & RM= Deadman 24,Reach-1,35181
     184     245     293     174     348     693     496
River Rch & RM= Deadman 24,Reach-1,30342
     258     351     425     256     511    1020     749
River Rch & RM= Deadman 24,Reach-1,27768
     292     397     481     290     578    1153     845
River Rch & RM= Deadman 24,Reach-1,21805
     314     428     520     313     625    1247     915
River Rch & RM= Deadman 24,Reach-1,19373
     351     480     584     352     702    1401    1031
River Rch & RM= Deadman 24,Reach-1,14802
     395     542     661     400     797    1591    1176
River Rch & RM= Deadman 24,Reach-1,7652
     400     546     664     400     798    1592    1169
Boundary for River Rch & Prof#=Deadman 24,Reach-1,1
Up Type=0
Dn Type=3
Dn Slope=0.005
Boundary for River Rch & Prof#=Deadman 24,Reach-1,2
Up Type=0
Dn Type=3
Dn Slope=0.005
Boundary for River Rch & Prof#=Deadman 24,Reach-1,3
Up Type=0
Dn Type=3
Dn Slope=0.005
Boundary for River Rch & Prof#=Deadman 24,Reach-1,4
Up Type=0
Dn Type=3
Dn Slope=0.005
Boundary for River Rch & Prof#=Deadman 24,Reach-1,5
Up Type=0
Dn Type=3
Dn Slope=0.005
Boundary for River Rch & Prof#=Deadman 24,Reach-1,6
Up Type=0
Dn Type=3
Dn Slope=0.005
Boundary for River Rch & Prof#=Deadman 24,Reach-1,7
Up Type=0
Dn Type=3
Dn Slope=0.005

--- Deadman 24.g01 (geometry) ---

Geom Title=Existing Conditions

River Reach=Deadman 24,Reach-1
Reach XY= 30
      1558005.00      6933838.00      1558949.14      6934035.93
      1560099.56      6933732.76      1560235.80      6933111.18
      1562984.77      6932837.50      1566008.41      6933680.23
      1566655.22      6932958.06      1565812.59      6931784.67
      1566702.55      6930993.47      1567118.73      6931024.80
      1567402.71      6930443.06      1568375.28      6929987.61
      1569404.90      6930430.68      1569870.34      6930087.96
      1570980.00      6930438.39      1572278.41      6930065.57
      1571812.31      6928838.11      1572204.13      6928298.33
      1571812.58      6927734.68      1572802.71      6926993.80
      1573272.15      6927021.56      1573294.68      6926399.10
      1573700.05      6926585.43      1573887.92      6927371.85
      1574457.67      6927393.29      1575004.75      6927931.03
      1576032.77      6927361.96      1576402.70      6926493.83
      1576855.00      6926781.13      1577755.00      6926488.00

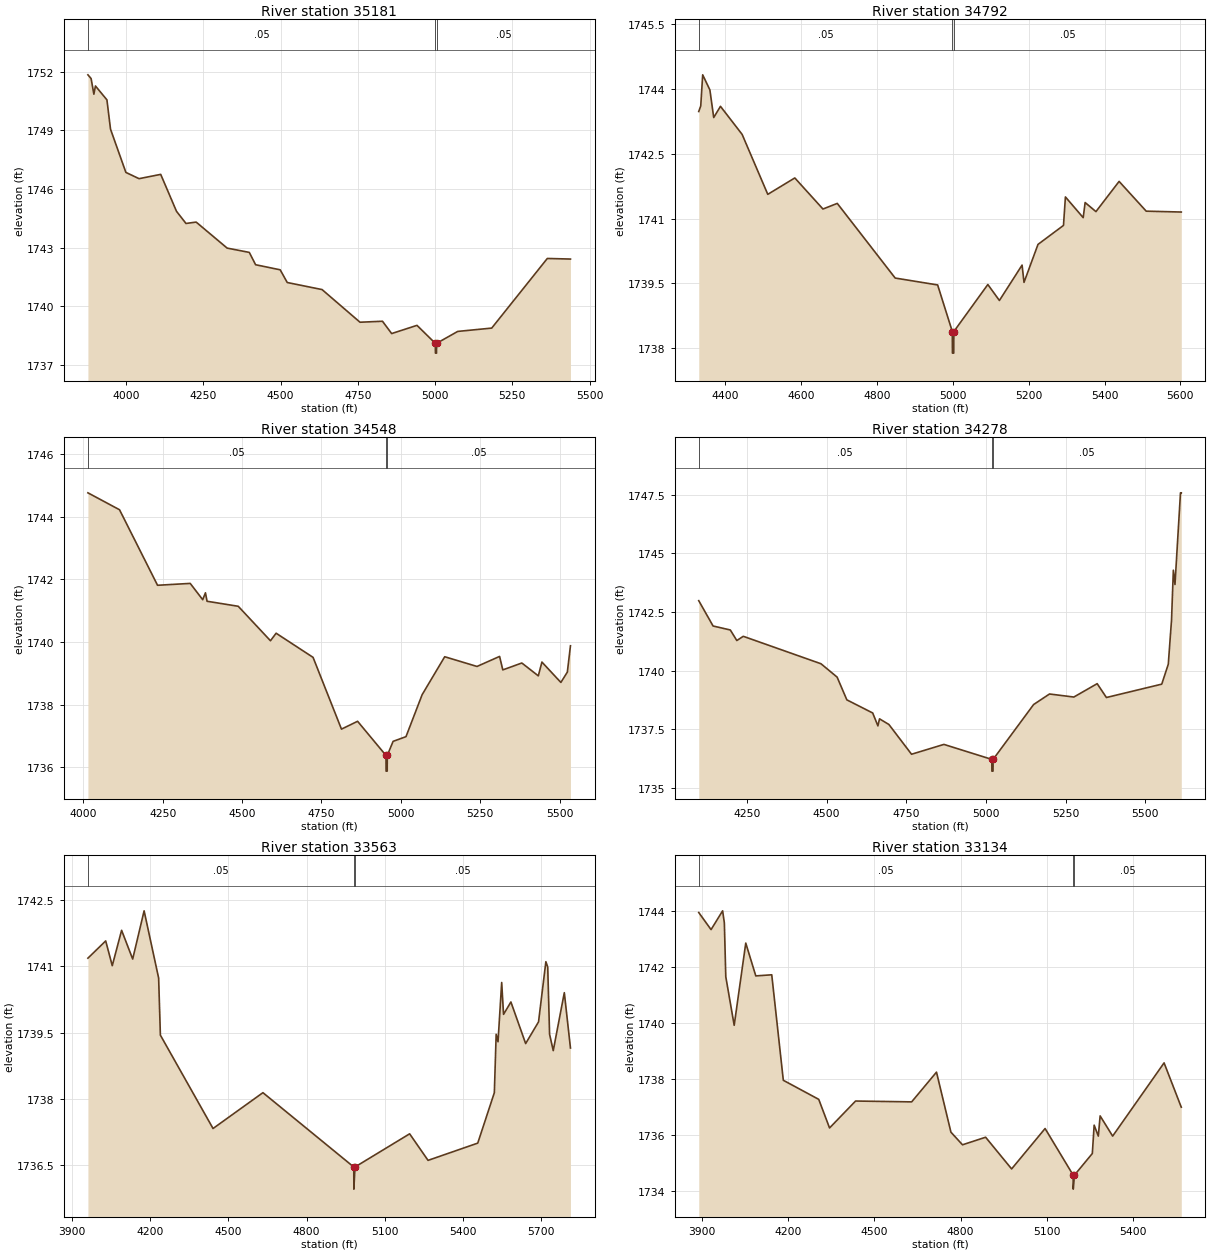
Type RM Length L Ch R = 1,35181,389,389,389
BEGIN DESCRIPTION:
Deadman 24 31.0
END DESCRIPTION:
XS GIS Cut Line= 3
      1557804.99      6934938.04      1558052.72      6933817.96
      1558047.96      6933403.14
#Sta/Elev= 30
  3876.2 1751.84  3886.5 1751.65  3895.5 1750.85  3900.6 1751.27  3937.7 1750.56
  3949.4 1749.06  3999.1 1746.85  4041.8 1746.53  4111.8 1746.75  4163.0 1744.86
  4193.7 1744.24  4226.6 1744.31  4326.9 1742.98  4398.6 1742.76  4419.0 1742.13
  4498.6 1741.87  4521.5 1741.22  4634.1 1740.86  4757.0 1739.19  4829.7 1739.24
  4859.4 1738.61  4941.4 1739.03  5000.8 1738.11  5001.1 1737.61  5004.6 1737.61
  5004.8 1738.11  5073.3 1738.72  5183.3 1738.89  5363.3 1742.45  5438.2 1742.42
#Mann=3,-1,0
  3876.2    0.05       0  5000.8   0.035       0  5004.8    0.05       0
Bank Sta=5000.8,5004.8
Exp/Cntr=0.3,0.1

Type RM Length L Ch R = 1,34792,244,244,244
BEGIN DESCRIPTION:
Mapping XS a427212f
END DESCRIPTION:
XS GIS Cut Line= 2
      1558238.74      6934696.83      1558478.31      6933446.88
#Sta/Elev= 30
  4329.7 1743.48  4335.0 1743.61  4340.1 1744.33  4359.1 1743.98  4369.2 1743.34
  4387.0 1743.60  4444.1 1742.95  4511.8 1741.56  4583.1 1741.94  4657.3 1741.22
  4695.1 1741.35  4847.8 1739.62  4959.8 1739.46  4998.5 1738.38  4998.8 1737.88
  5002.3 1737.88  5002.5 1738.38  5092.2 1739.47  5122.7 1739.10  5182.5 1739.92
  5187.6 1739.52  5224.5 1740.40  5291.7 1740.84  5296.8 1741.50  5343.7 1741.02
  5348.8 1741.37  5377.3 1741.16  5438.4 1741.86  5509.9 1741.17  5602.4 1741.15
#Mann=3,-1,0
  4329.7    0.05       0  4998.5   0.035       0  5002.5    0.05       0
Bank Sta=4998.5,5002.5
Exp/Cntr=0.3,0.1

Type RM Length L Ch R = 1,34548,270,270,270
BEGIN DESCRIPTION:
Mapping XS 9a7c76e8
END DESCRIPTION:
XS GIS Cut Line= 2
      1558392.55      6934973.78      1558666.90      6933478.34
#Sta/Elev= 30
  4014.1 1744.76  4113.7 1744.22  4233.5 1741.81  4336.4 1741.87  4375.8 1741.35
  4384.4 1741.57  4389.5 1741.30  4487.7 1741.14  4589.3 1740.04  4607.1 1740.28
  4723.5 1739.51  4813.0 1737.22  4863.8 1737.47  4953.3 1736.38  4953.6 1735.88
  4957.1 1735.88  4957.3 1736.38  4975.7 1736.83  5016.3 1736.98  5067.2 1738.32
  5138.3 1739.53  5240.0 1739.22  5311.2 1739.54  5321.3 1739.11  5381.3 1739.33
  5433.2 1738.92  5444.6 1739.36  5504.3 1738.71  5524.7 1739.04  5534.5 1739.88
#Mann=3,-1,0
  4014.1    0.05       0  4953.3   0.035       0  4957.3    0.05       0
Bank Sta=4953.3,4957.3
Exp/Cntr=0.3,0.1

Type RM Length L Ch R = 1,34278,715,715,715
BEGIN DESCRIPTION:
Deadman 24 30.0
END DESCRIPTION:
XS GIS Cut Line= 3
      1558671.87      6934925.70      1558829.87      6934032.51
      1558705.01      6933438.04
#Sta/Elev= 30
  4098.5 1742.98  4143.5 1741.90  4197.6 1741.73  4218.0 1741.28  4238.3 1741.46
  4482.1 1740.29  4532.8 1739.72  4563.3 1738.75  4644.5 1738.19  4660.8 1737.64
  4665.9 1737.94  4695.3 1737.70  4766.4 1736.43  4868.0 1736.85  5018.4 1736.21
  5018.6 1735.71  5022.1 1735.71  5022.4 1736.21  5149.5 1738.55  5199.4 1739.00
  5275.8 1738.87  5349.0 1739.44  5378.0 1738.85  5551.7 1739.42  5572.2 1740.27
  5582.4 1742.16  5588.1 1744.28  5593.2 1743.67  5610.5 1747.58  5613.0 1747.58
#Mann=3,-1,0
  4098.5    0.05       0  5018.4   0.035       0  5022.4    0.05       0
Bank Sta=5018.4,5022.4
Exp/Cntr=0.3,0.1

Type RM Length L Ch R = 1,33563,429,429,429
BEGIN DESCRIPTION:
Deadman 24 29.0
END DESCRIPTION:
XS GIS Cut Line= 3
      1559812.51      6934769.48      1559455.00      6933788.00
      1558882.33      6933217.23
#Sta/Elev= 30
  3960.3 1741.18  4028.6 1741.57  4053.8 1741.01  4089.7 1741.81  4132.2 1741.16
  4176.1 1742.25  4231.9 1740.73  4238.6 1739.44  4440.8 1737.33  4632.4 1738.14
  4981.3 1736.46  4981.6 1735.96  4985.9 1736.46  5195.8 1737.21  5266.5 1736.61
  5457.4 1737.00  5521.1 1738.14  5528.1 1739.46  5535.2 1739.29  5549.3 1740.63
  5556.4 1739.91  5584.7 1740.19  5641.3 1739.25  5690.8 1739.74  5719.0 1741.10
  5726.1 1740.98  5733.2 1739.46  5747.3 1739.09  5789.8 1740.40  5813.4 1739.15
#Mann=3,-1,0
  3960.3    0.05       0  4981.3   0.035       0  4985.9    0.05       0
Bank Sta=4981.3,4985.9
Exp/Cntr=0.3,0.1

Type RM Length L Ch R = 1,33134,497,497,497
BEGIN DESCRIPTION:
Deadman 24 28.0
END DESCRIPTION:
XS GIS Cut Line= 3
      1559958.32      6934800.66      1559855.00      6933688.00
      1559410.63      6933348.10
#Sta/Elev= 30
  3890.3 1743.93  3933.1 1743.32  3973.3 1743.99  3979.3 1743.56  3984.3 1741.64
  4013.5 1739.91  4053.7 1742.84  4088.6 1741.67  4144.0 1741.71  4184.2 1737.95
  4307.3 1737.27  4344.9 1736.25  4435.3 1737.21  4630.2 1737.18  4716.5 1738.24
  4766.7 1736.10  4806.9 1735.65  4887.2 1735.92  4977.6 1734.79  5093.9 1736.23
  5191.4 1734.57  5191.7 1734.07  5196.0 1734.57  5258.1 1735.34  5264.4 1736.35
  5278.9 1735.96  5285.2 1736.68  5328.7 1735.96  5507.4 1738.57  5567.2 1736.99
#Mann=3,-1,0
  3890.3    0.05       0  5191.4   0.035       0  5196.0    0.05       0
Bank Sta=5191.4,5196
Exp/Cntr=0.3,0.1

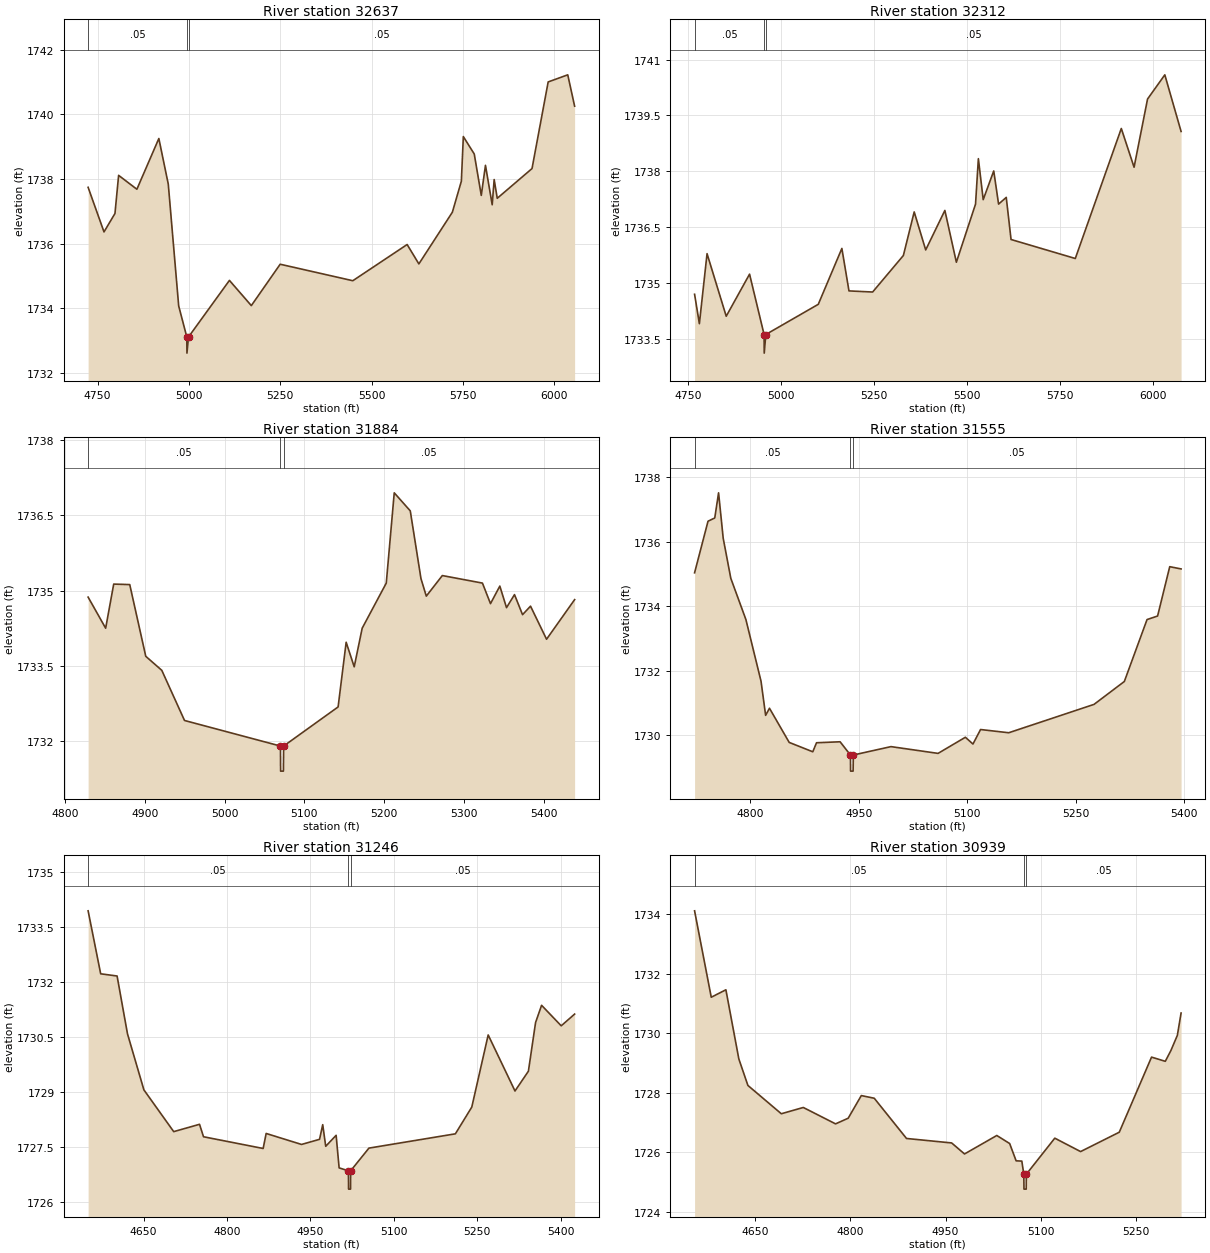
Type RM Length L Ch R = 1,32637,325,325,325
BEGIN DESCRIPTION:
Mapping XS 74f4dbfc
END DESCRIPTION:
XS GIS Cut Line= 3
      1560201.36      6933781.48      1560207.37      6933565.09
      1559167.50      6933162.37
#Sta/Elev= 30
  4724.0 1737.74  4767.5 1736.36  4797.5 1736.93  4807.5 1738.11  4857.5 1737.68
  4917.6 1739.25  4943.4 1737.84  4971.9 1734.07  4994.1 1733.11  4994.5 1732.61
  4998.8 1733.11  5110.8 1734.86  5170.7 1734.08  5249.7 1735.36  5448.5 1734.85
  5597.2 1735.97  5629.3 1735.37  5721.0 1736.97  5745.6 1737.93  5751.0 1739.31
  5780.9 1738.77  5800.1 1737.49  5811.6 1738.42  5830.0 1737.20  5835.4 1737.98
  5843.8 1737.40  5939.0 1738.32  5983.2 1741.00  6036.8 1741.22  6055.6 1740.25
#Mann=3,-1,0
  4724.0    0.05       0  4994.1    0.05       0  4998.8    0.05       0
Bank Sta=4994.1,4998.8
Exp/Cntr=0.3,0.1

Type RM Length L Ch R = 1,32312,428,428,428
BEGIN DESCRIPTION:
Mapping XS 2c1154e4
END DESCRIPTION:
XS GIS Cut Line= 2
      1560297.50      6933327.65      1559029.17      6933012.07
#Sta/Elev= 30
  4767.2 1734.70  4780.1 1733.91  4800.7 1735.79  4852.2 1734.11  4914.9 1735.24
  4953.9 1733.62  4954.3 1733.12  4958.6 1733.62  5099.5 1734.43  5162.9 1735.93
  5182.0 1734.79  5245.5 1734.76  5328.1 1735.74  5357.2 1736.91  5388.1 1735.89
  5439.6 1736.95  5470.5 1735.56  5522.0 1737.12  5529.6 1738.34  5542.6 1737.24
  5570.9 1738.01  5583.9 1737.12  5604.5 1737.30  5617.4 1736.17  5790.0 1735.66
  5913.6 1739.15  5947.9 1738.11  5984.1 1739.94  6030.5 1740.59  6074.2 1739.07
#Mann=3,-1,0
  4767.2    0.05       0  4953.9   0.035       0  4958.6    0.05       0
Bank Sta=4953.9,4958.6
Exp/Cntr=0.3,0.1

Type RM Length L Ch R = 1,31884,329,329,329
BEGIN DESCRIPTION:
Deadman 24 26.0
END DESCRIPTION:
XS GIS Cut Line= 2
      1560442.78      6933269.89      1560380.00      6932663.02
#Sta/Elev= 30
  4828.8 1734.87  4850.8 1734.25  4860.9 1735.13  4881.0 1735.12  4901.1 1733.69
  4921.2 1733.41  4949.7 1732.41  5070.0 1731.90  5070.2 1731.40  5073.7 1731.40
  5074.0 1731.90  5142.3 1732.68  5152.4 1733.97  5162.5 1733.48  5172.5 1734.25
  5202.7 1735.15  5212.7 1736.95  5232.8 1736.59  5246.2 1735.24  5252.9 1734.89
  5273.0 1735.30  5323.3 1735.15  5333.4 1734.74  5345.1 1735.09  5353.5 1734.66
  5363.5 1734.92  5373.6 1734.52  5383.6 1734.69  5403.7 1734.03  5438.9 1734.82
#Mann=3,-1,0
  4828.8    0.05       0  5070.0    0.05       0  5074.0    0.05       0
Bank Sta=5070,5074
Exp/Cntr=0.3,0.1

Type RM Length L Ch R = 1,31555,309,309,309
BEGIN DESCRIPTION:
Deadman 24 25.0
END DESCRIPTION:
XS GIS Cut Line= 2
      1560829.49      6933355.80      1560630.01      6932713.04
#Sta/Elev= 30
  4722.8 1735.04  4741.4 1736.64  4750.7 1736.74  4756.0 1737.52  4762.4 1736.11
  4772.9 1734.87  4793.8 1733.59  4814.7 1731.68  4821.1 1730.62  4826.4 1730.84
  4853.7 1729.78  4886.3 1729.49  4891.5 1729.77  4924.1 1729.80  4938.4 1729.39
  4938.6 1728.89  4942.1 1728.89  4942.4 1729.39  4994.5 1729.65  5059.6 1729.44
  5097.4 1729.94  5107.9 1729.73  5118.4 1730.18  5157.4 1730.08  5275.4 1730.96
  5317.3 1731.67  5348.7 1733.59  5363.3 1733.70  5380.1 1735.23  5395.8 1735.16
#Mann=3,-1,0
  4722.8    0.05       0  4938.4    0.05       0  4942.4    0.05       0
Bank Sta=4938.4,4942.4
Exp/Cntr=0.3,0.1

Type RM Length L Ch R = 1,31246,307,307,307
BEGIN DESCRIPTION:
Deadman 24 24.0
END DESCRIPTION:
XS GIS Cut Line= 2
      1561208.62      6933423.60      1560879.99      6932612.99
#Sta/Elev= 30
  4550.3 1733.95  4572.9 1732.23  4602.4 1732.17  4621.1 1730.59  4650.6 1729.06
  4704.2 1727.92  4750.6 1728.12  4757.8 1727.78  4865.0 1727.46  4870.4 1727.87
  4934.0 1727.57  4966.4 1727.71  4972.1 1728.11  4977.5 1727.52  4996.2 1727.82
  5001.6 1726.93  5018.3 1726.85  5018.6 1726.35  5022.1 1726.35  5022.3 1726.85
  5055.2 1727.47  5210.6 1727.86  5240.1 1728.59  5269.6 1730.56  5317.8 1729.03
  5341.9 1729.57  5354.8 1730.90  5365.6 1731.37  5400.9 1730.81  5425.0 1731.13
#Mann=3,-1,0
  4550.3    0.05       0  5018.3    0.05       0  5022.3    0.05       0
Bank Sta=5018.3,5022.3
Exp/Cntr=0.3,0.1

Type RM Length L Ch R = 1,30939,265,265,265
BEGIN DESCRIPTION:
Mapping XS b49ca992
END DESCRIPTION:
XS GIS Cut Line= 2
      1561264.77      6933436.60      1561405.25      6932682.17
#Sta/Elev= 30
  4554.1 1734.11  4580.4 1731.21  4603.5 1731.46  4623.9 1729.14  4638.2 1728.25
  4690.9 1727.30  4725.6 1727.51  4776.5 1726.96  4796.4 1727.15  4817.1 1727.91
  4837.5 1727.82  4888.4 1726.47  4959.6 1726.32  4979.9 1725.95  5030.8 1726.57
  5051.1 1726.30  5061.3 1725.72  5070.3 1725.71  5073.4 1725.27  5073.7 1724.77
  5077.2 1724.77  5077.4 1725.27  5122.3 1726.48  5163.0 1726.03  5224.0 1726.68
  5274.9 1729.20  5296.6 1729.06  5305.4 1729.42  5315.6 1729.93  5321.5 1730.68
#Mann=3,-1,0
  4554.1    0.05       0  5073.4    0.05       0  5077.4    0.05       0
Bank Sta=5073.4,5077.4
Exp/Cntr=0.3,0.1

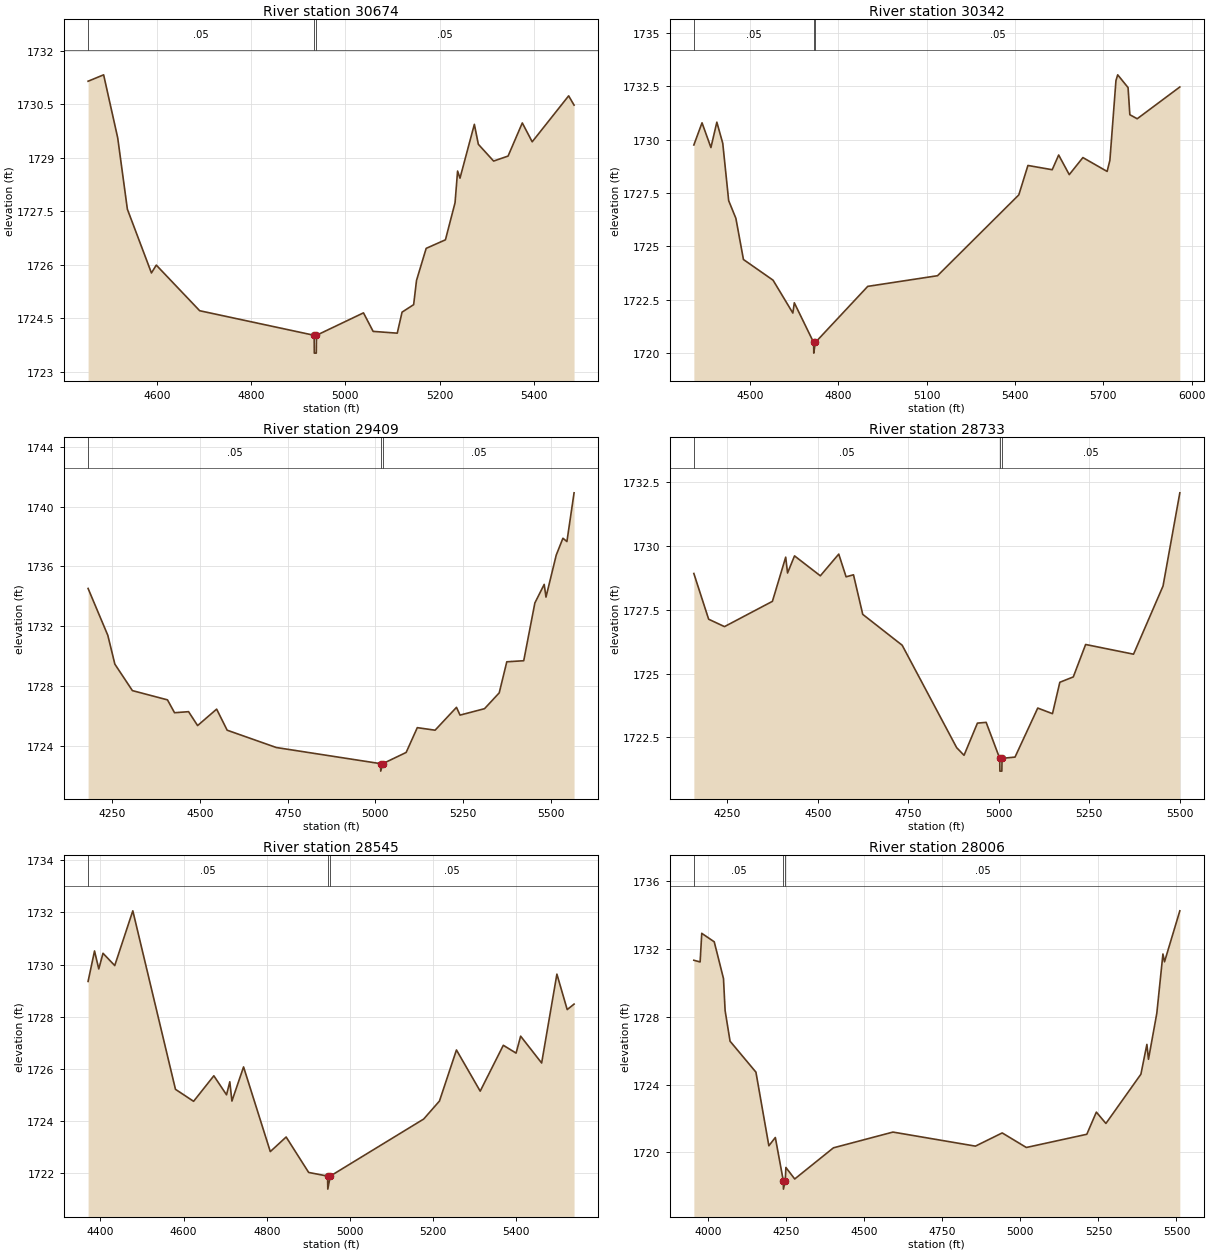
Type RM Length L Ch R = 1,30674,332,332,332
BEGIN DESCRIPTION:
Mapping XS 10cfadcf
END DESCRIPTION:
XS GIS Cut Line= 2
      1561493.94      6933509.50      1561712.27      6932501.06
#Sta/Elev= 30
  4453.8 1731.15  4486.8 1731.33  4516.7 1729.56  4537.2 1727.56  4588.3 1725.77
  4598.6 1725.99  4690.7 1724.71  4933.8 1724.02  4934.1 1723.52  4938.3 1723.52
  4938.7 1724.02  5038.5 1724.65  5059.0 1724.13  5110.2 1724.08  5120.4 1724.67
  5145.0 1724.88  5151.1 1725.56  5171.6 1726.46  5212.5 1726.70  5232.9 1727.74
  5238.3 1728.63  5243.4 1728.43  5273.9 1729.94  5282.4 1729.38  5314.8 1728.91
  5345.5 1729.05  5375.7 1729.98  5396.7 1729.45  5474.1 1730.74  5485.6 1730.48
#Mann=3,-1,0
  4453.8    0.05       0  4933.8    0.05       0  4938.7    0.05       0
Bank Sta=4933.8,4938.7
Exp/Cntr=0.3,0.1

Type RM Length L Ch R = 1,30342,933,933,933
BEGIN DESCRIPTION:
Deadman 24 23.0
END DESCRIPTION:
XS GIS Cut Line= 3
      1561924.50      6933665.66      1561855.00      6932988.00
      1562091.17      6932047.52
#Sta/Elev= 30
  4309.0 1729.75  4336.8 1730.79  4367.0 1729.63  4387.1 1730.82  4407.2 1729.83
  4427.3 1727.14  4451.8 1726.31  4477.5 1724.38  4578.1 1723.41  4645.3 1721.87
  4650.3 1722.35  4715.9 1720.49  4716.4 1719.99  4721.6 1720.49  4899.7 1723.12
  5136.8 1723.62  5412.9 1727.41  5443.9 1728.79  5526.4 1728.59  5548.3 1729.28
  5584.3 1728.36  5630.6 1729.16  5712.9 1728.51  5722.3 1729.03  5742.9 1732.77
  5748.9 1733.04  5784.1 1732.44  5790.1 1731.17  5815.1 1730.98  5959.9 1732.47
#Mann=3,-1,0
  4309.0    0.05       0  4715.9    0.05       0  4721.6    0.05       0
Bank Sta=4715.9,4721.6
Exp/Cntr=0.3,0.1

Type RM Length L Ch R = 1,29409,676,676,676
BEGIN DESCRIPTION:
Deadman 24 22.0
END DESCRIPTION:
XS GIS Cut Line= 3
      1562514.77      6933714.27      1562555.00      6932888.00
      1562454.99      6932337.97
#Sta/Elev= 30
  4180.5 1734.53  4236.8 1731.39  4256.9 1729.46  4306.9 1727.69  4407.0 1727.07
  4427.1 1726.21  4467.1 1726.28  4492.9 1725.35  4547.2 1726.45  4577.2 1725.04
  4717.4 1723.88  5014.8 1722.80  5015.3 1722.30  5021.1 1722.80  5087.8 1723.55
  5119.6 1725.21  5170.4 1725.04  5231.4 1726.57  5241.5 1726.05  5311.4 1726.48
  5353.3 1727.54  5374.9 1729.62  5423.2 1729.69  5455.0 1733.56  5481.6 1734.80
  5486.7 1733.95  5515.9 1736.76  5535.0 1737.89  5546.4 1737.67  5566.8 1740.93
#Mann=3,-1,0
  4180.5    0.05       0  5014.8    0.05       0  5021.1    0.05       0
Bank Sta=5014.8,5021.1
Exp/Cntr=0.3,0.1

Type RM Length L Ch R = 1,28733,188,188,188
BEGIN DESCRIPTION:
Mapping XS 4e9fec31
END DESCRIPTION:
XS GIS Cut Line= 2
      1562901.92      6933721.19      1563155.27      6932402.40
#Sta/Elev= 30
  4157.7 1728.92  4198.6 1727.13  4242.4 1726.84  4374.8 1727.83  4411.5 1729.56
  4416.6 1728.94  4435.9 1729.61  4507.2 1728.83  4558.1 1729.68  4578.4 1728.79
  4598.8 1728.87  4624.4 1727.32  4733.4 1726.11  4883.9 1722.10  4904.3 1721.80
  4941.3 1723.06  4965.4 1723.09  5002.9 1721.68  5003.4 1721.18  5008.8 1721.18
  5009.3 1721.68  5045.2 1721.73  5108.0 1723.65  5148.7 1723.43  5169.0 1724.66
  5206.2 1724.87  5240.3 1726.14  5372.7 1725.76  5454.2 1728.43  5500.6 1732.08
#Mann=3,-1,0
  4157.7    0.05       0  5002.9    0.05       0  5009.3    0.05       0
Bank Sta=5002.9,5009.3
Exp/Cntr=0.3,0.1

Type RM Length L Ch R = 1,28545,539,539,539
BEGIN DESCRIPTION:
Mapping XS 9c9340c5
END DESCRIPTION:
XS GIS Cut Line= 2
      1563075.54      6933603.09      1563328.77      6932461.85
#Sta/Elev= 30
  4370.2 1729.35  4385.7 1730.52  4395.9 1729.83  4406.1 1730.43  4434.3 1729.96
  4477.8 1732.06  4580.4 1725.21  4624.0 1724.75  4672.7 1725.73  4703.2 1725.00
  4711.1 1725.50  4716.2 1724.76  4744.2 1726.07  4808.5 1722.82  4846.6 1723.38
  4900.8 1722.02  4946.3 1721.88  4946.8 1721.38  4952.7 1721.88  5177.5 1724.07
  5215.4 1724.76  5256.3 1726.72  5313.4 1725.14  5369.0 1726.90  5399.7 1726.60
  5410.7 1727.25  5461.2 1726.22  5497.9 1729.63  5522.7 1728.27  5539.2 1728.48
#Mann=3,-1,0
  4370.2    0.05       0  4946.3    0.05       0  4952.7    0.05       0
Bank Sta=4946.3,4952.7
Exp/Cntr=0.3,0.1

Type RM Length L Ch R = 1,28006,238,238,238
BEGIN DESCRIPTION:
Mapping XS cb37ae31
END DESCRIPTION:
XS GIS Cut Line= 4
      1563003.05      6933838.89      1563406.68      6933730.39
      1563580.29      6933539.42      1563749.56      6932675.69
#Sta/Elev= 30
  3954.6 1731.34  3974.7 1731.24  3979.9 1732.93  4019.9 1732.43  4049.5 1730.26
  4054.7 1728.37  4070.5 1726.56  4153.4 1724.73  4194.8 1720.38  4215.5 1720.87
  4241.0 1718.32  4241.5 1717.82  4247.4 1718.32  4249.3 1719.10  4277.6 1718.42
  4401.6 1720.26  4592.2 1721.19  4856.3 1720.36  4942.0 1721.14  5019.3 1720.28
  5212.9 1721.06  5243.5 1722.37  5274.1 1721.70  5386.2 1724.61  5405.3 1726.37
  5410.4 1725.49  5437.1 1728.21  5456.7 1731.71  5461.8 1731.25  5510.8 1734.26
#Mann=3,-1,0
  3954.6    0.05       0  4241.0    0.05       0  4247.4    0.05       0
Bank Sta=4241,4247.4
Exp/Cntr=0.3,0.1

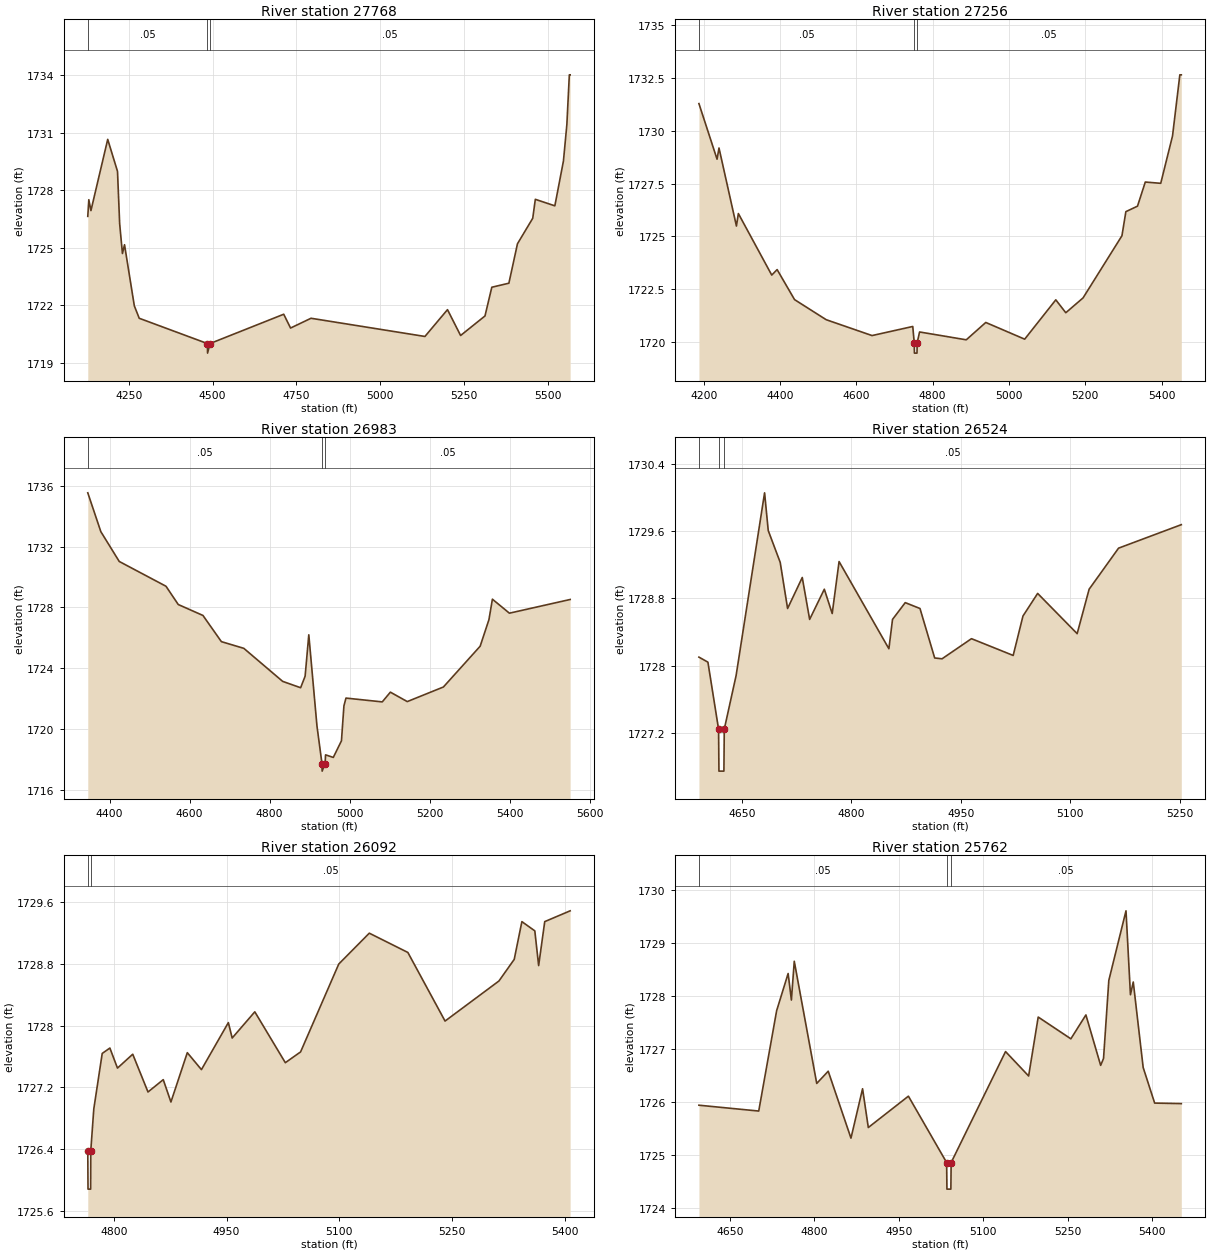
Type RM Length L Ch R = 1,27768,512,512,512
BEGIN DESCRIPTION:
Mapping XS 6b1daaf4
END DESCRIPTION:
XS GIS Cut Line= 3
      1563892.82      6934034.24      1563766.92      6933864.94
      1563988.27      6932658.36
#Sta/Elev= 30
  4128.1 1726.64  4131.2 1727.51  4137.5 1726.94  4187.5 1730.66  4216.7 1728.99
  4223.1 1726.26  4231.4 1724.70  4237.6 1725.16  4266.8 1721.97  4281.4 1721.32
  4484.6 1720.00  4485.1 1719.50  4492.3 1720.00  4712.1 1721.53  4732.5 1720.81
  4793.5 1721.32  5133.0 1720.37  5200.2 1721.77  5239.3 1720.42  5312.0 1721.44
  5332.3 1722.94  5383.2 1723.15  5408.8 1725.21  5454.3 1726.54  5462.0 1727.53
  5520.2 1727.19  5545.8 1729.53  5556.0 1731.43  5563.4 1734.03  5565.8 1734.03
#Mann=3,-1,0
  4128.1    0.05       0  4484.6    0.05       0  4492.3    0.05       0
Bank Sta=4484.6,4492.3
Exp/Cntr=0.3,0.1

Type RM Length L Ch R = 1,27256,273,273,273
BEGIN DESCRIPTION:
Mapping XS 2b6f0c5e
END DESCRIPTION:
XS GIS Cut Line= 2
      1564179.69      6933985.11      1564429.70      6932745.47
#Sta/Elev= 30
  4187.2 1731.28  4234.7 1728.65  4239.8 1729.18  4285.5 1725.49  4290.6 1726.08
  4378.1 1723.17  4392.2 1723.43  4437.9 1722.01  4520.9 1721.06  4641.1 1720.31
  4747.8 1720.74  4751.6 1719.98  4752.1 1719.48  4758.9 1719.48  4759.4 1719.98
  4765.7 1720.48  4888.1 1720.11  4939.2 1720.93  5041.2 1720.14  5122.8 1722.00
  5149.0 1721.39  5194.2 1722.09  5296.2 1725.03  5306.5 1726.17  5337.0 1726.43
  5357.4 1727.57  5397.9 1727.51  5428.8 1729.75  5448.0 1732.64  5451.8 1732.64
#Mann=3,-1,0
  4187.2    0.05       0  4751.6    0.05       0  4759.4    0.05       0
Bank Sta=4751.6,4759.4
Exp/Cntr=0.3,0.1

Type RM Length L Ch R = 1,26983,459,459,459
BEGIN DESCRIPTION:
Mapping XS ecc35c16
END DESCRIPTION:
XS GIS Cut Line= 2
      1564384.57      6934019.74      1564620.34      6932837.42
#Sta/Elev= 30
  4345.4 1735.53  4378.0 1732.98  4424.0 1731.02  4540.9 1729.39  4571.5 1728.19
  4633.3 1727.47  4679.3 1725.75  4735.4 1725.31  4832.4 1723.14  4877.4 1722.72
  4888.6 1723.48  4897.8 1726.20  4918.2 1720.21  4930.7 1717.74  4931.2 1717.24
  4938.5 1717.74  4939.7 1718.31  4959.0 1718.14  4979.4 1719.23  4985.6 1721.53
  4990.7 1722.04  5081.4 1721.79  5101.7 1722.43  5143.9 1721.81  5234.3 1722.77
  5326.1 1725.45  5348.1 1727.20  5356.7 1728.54  5399.2 1727.62  5551.0 1728.52
#Mann=3,-1,0
  4345.4    0.05       0  4930.7    0.05       0  4938.5    0.05       0
Bank Sta=4930.7,4938.5
Exp/Cntr=0.3,0.1

Type RM Length L Ch R = 1,26524,432,432,432
BEGIN DESCRIPTION:
Mapping XS 2cf2a99f
END DESCRIPTION:
XS GIS Cut Line= 2
      1564868.93      6933858.54      1564947.01      6933202.67
#Sta/Elev= 30
  4591.4 1728.10  4603.7 1728.04  4618.3 1727.24  4618.8 1726.74  4625.6 1726.74
  4626.1 1727.24  4642.3 1727.88  4681.3 1730.06  4686.3 1729.61  4702.7 1729.23
  4712.8 1728.68  4732.9 1729.05  4743.0 1728.55  4763.1 1728.91  4773.9 1728.62
  4783.3 1729.24  4851.5 1728.20  4856.5 1728.55  4873.9 1728.75  4894.1 1728.68
  4914.2 1728.09  4924.3 1728.08  4964.6 1728.32  5021.7 1728.12  5035.1 1728.59
  5055.2 1728.86  5109.3 1728.38  5125.7 1728.91  5166.0 1729.40  5251.9 1729.68
#Mann=3,-1,0
  4591.4    0.05       0  4618.3    0.05       0  4626.1    0.05       0
Bank Sta=4618.3,4626.1
Exp/Cntr=0.3,0.1

Type RM Length L Ch R = 1,26092,330,330,330
BEGIN DESCRIPTION:
Mapping XS 9df33d7c
END DESCRIPTION:
XS GIS Cut Line= 2
      1565227.96      6933896.96      1565337.69      6933264.71
#Sta/Elev= 30
  4765.3 1726.38  4765.6 1725.88  4769.1 1725.88  4769.3 1726.38  4773.3 1726.92
  4784.5 1727.64  4794.7 1727.71  4804.8 1727.45  4825.1 1727.63  4845.4 1727.14
  4865.7 1727.30  4875.9 1727.01  4897.7 1727.65  4916.5 1727.43  4952.3 1728.04
  4957.4 1727.84  4987.5 1728.18  5028.1 1727.52  5048.4 1727.66  5099.2 1728.80
  5139.8 1729.20  5191.1 1728.95  5240.6 1728.06  5312.3 1728.58  5332.6 1728.86
  5342.8 1729.35  5360.0 1729.23  5365.1 1728.78  5373.2 1729.35  5407.0 1729.49
#Mann=2,-1,0
  4765.3    0.05       0  4769.3    0.05       0
Bank Sta=4765.3,4769.3
Exp/Cntr=0.3,0.1

Type RM Length L Ch R = 1,25762,300,300,300
BEGIN DESCRIPTION:
Mapping XS 68562d87
END DESCRIPTION:
XS GIS Cut Line= 2
      1565519.97      6934113.74      1565675.95      6933271.46
#Sta/Elev= 30
  4595.3 1725.94  4701.5 1725.83  4733.3 1727.72  4753.7 1728.42  4759.5 1727.92
  4764.6 1728.65  4804.5 1726.35  4824.9 1726.58  4865.3 1725.32  4885.9 1726.25
  4896.1 1725.52  4967.3 1726.11  5035.2 1724.86  5035.7 1724.36  5042.7 1724.36
  5043.2 1724.86  5139.8 1726.95  5180.8 1726.49  5197.8 1727.60  5255.8 1727.19
  5282.5 1727.64  5308.7 1726.69  5313.8 1726.82  5323.2 1728.29  5353.7 1729.60
  5361.6 1728.02  5366.6 1728.26  5384.2 1726.65  5404.6 1725.98  5451.9 1725.97
#Mann=3,-1,0
  4595.3    0.05       0  5035.2    0.03       0  5043.2    0.05       0
Bank Sta=5035.2,5043.2
Exp/Cntr=0.3,0.1

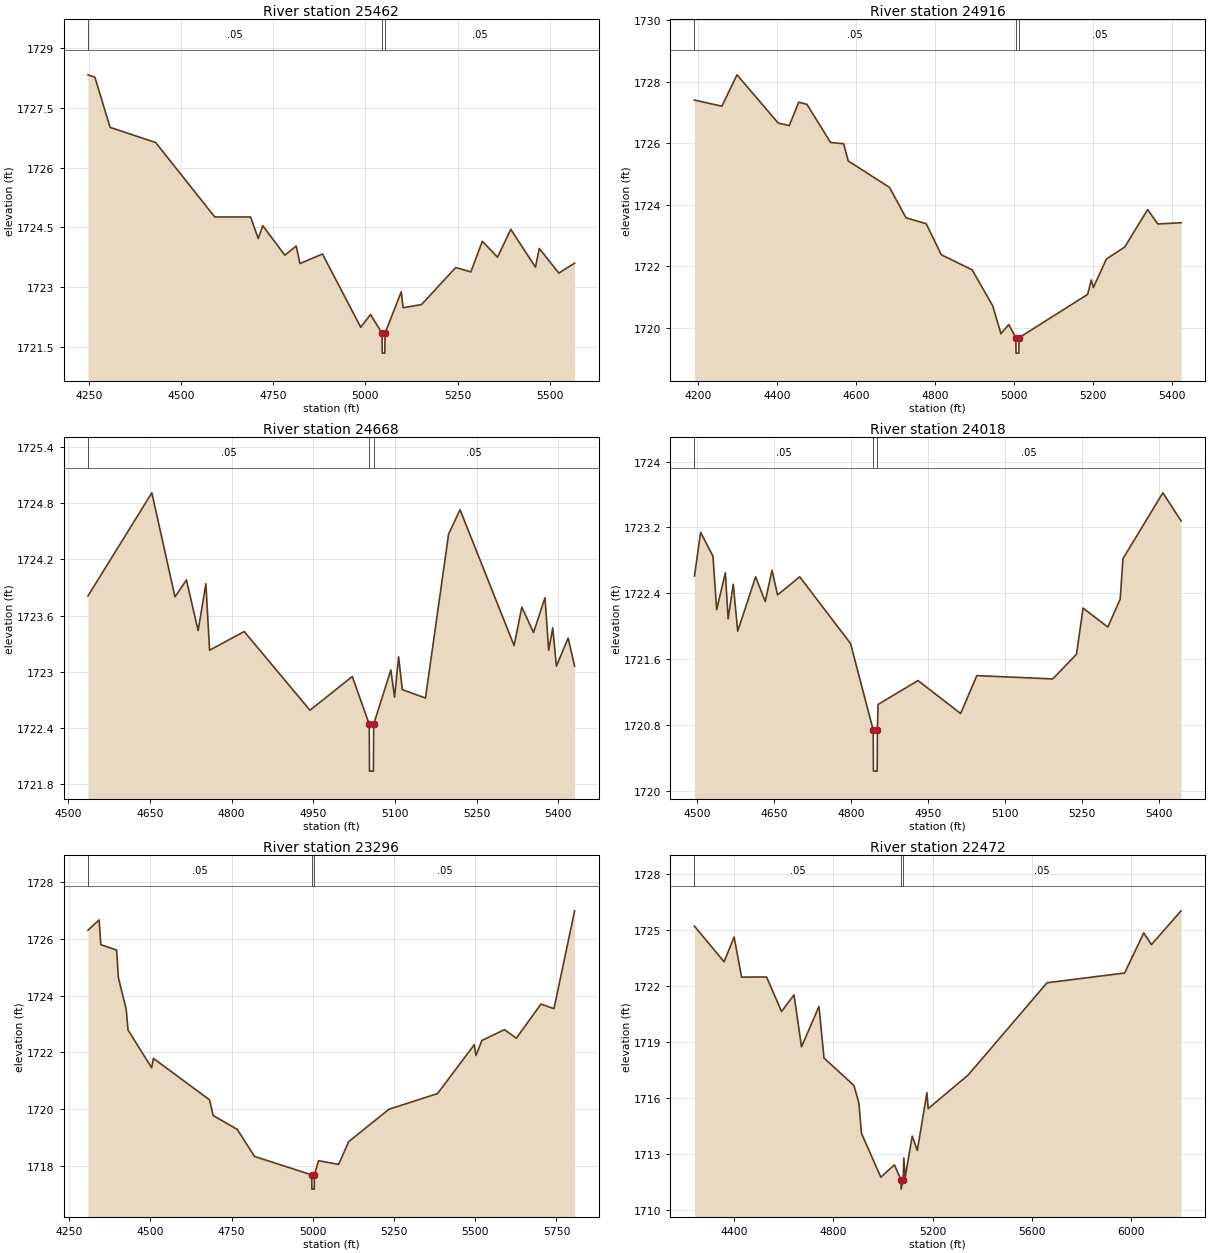
Type RM Length L Ch R = 1,25462,546,546,546
BEGIN DESCRIPTION:
Mapping XS 742c9280
END DESCRIPTION:
XS GIS Cut Line= 2
      1565648.45      6934346.18      1565960.95      6933064.94
#Sta/Elev= 30
  4248.2 1728.33  4266.9 1728.27  4308.1 1727.01  4431.6 1726.63  4591.8 1724.76
  4688.9 1724.76  4709.5 1724.22  4722.0 1724.54  4781.6 1723.80  4812.5 1724.03
  4822.7 1723.59  4883.6 1723.83  4987.4 1721.99  5013.8 1722.31  5045.2 1721.84
  5045.7 1721.34  5052.7 1721.34  5053.2 1721.84  5097.1 1722.88  5102.3 1722.48
  5152.1 1722.56  5244.8 1723.49  5285.9 1723.38  5316.8 1724.15  5358.0 1723.75
  5394.1 1724.45  5460.9 1723.50  5471.2 1723.97  5524.3 1723.35  5567.0 1723.60
#Mann=3,-1,0
  4248.2    0.05       0  5045.2    0.04       0  5053.2    0.05       0
Bank Sta=5045.2,5053.2
Exp/Cntr=0.3,0.1

Type RM Length L Ch R = 1,24916,248,248,248
BEGIN DESCRIPTION:
Mapping XS 50ea41ec
END DESCRIPTION:
XS GIS Cut Line= 2
      1566509.57      6934290.64      1566155.84      6933111.55
#Sta/Elev= 30
  4191.1 1727.40  4260.5 1727.20  4298.7 1728.22  4403.1 1726.65  4431.0 1726.57
  4454.9 1727.33  4475.7 1727.26  4535.4 1726.02  4568.4 1725.98  4580.1 1725.42
  4684.5 1724.56  4726.3 1723.57  4777.3 1723.38  4815.5 1722.37  4893.4 1721.88
  4945.6 1720.71  4966.4 1719.80  4986.1 1720.10  5004.1 1719.67  5004.6 1719.17
  5011.7 1719.17  5012.2 1719.67  5185.7 1721.08  5194.9 1721.55  5200.1 1721.30
  5233.1 1722.23  5279.6 1722.62  5337.5 1723.84  5363.2 1723.37  5422.1 1723.41
#Mann=3,-1,0
  4191.1    0.05       0  5004.1    0.04       0  5012.2    0.05       0
Bank Sta=5004.1,5012.2
Exp/Cntr=0.3,0.1

Type RM Length L Ch R = 1,24668,650,650,650
BEGIN DESCRIPTION:
Mapping XS e0e581e5
END DESCRIPTION:
XS GIS Cut Line= 2
      1566800.79      6933747.76      1566193.44      6933092.69
#Sta/Elev= 30
  4536.5 1723.81  4653.7 1724.91  4696.2 1723.80  4717.2 1723.98  4738.7 1723.44
  4752.9 1723.94  4759.7 1723.23  4823.2 1723.43  4944.0 1722.59  5021.7 1722.95
  5052.8 1722.44  5053.3 1721.94  5060.4 1721.94  5060.9 1722.44  5092.5 1723.02
  5099.3 1722.73  5106.7 1723.16  5113.5 1722.81  5156.0 1722.72  5198.5 1724.47
  5219.5 1724.73  5318.7 1723.28  5332.9 1723.69  5354.4 1723.42  5375.4 1723.79
  5382.2 1723.23  5389.6 1723.47  5396.4 1723.06  5417.9 1723.36  5429.8 1723.06
#Mann=3,-1,0
  4536.5    0.05       0  5052.8    0.04       0  5060.9    0.05       0
Bank Sta=5052.8,5060.9
Exp/Cntr=0.3,0.1

Type RM Length L Ch R = 1,24018,722,722,722
BEGIN DESCRIPTION:
Mapping XS 0d7983e2
END DESCRIPTION:
XS GIS Cut Line= 2
      1567055.12      6932680.13      1566176.09      6933035.93
#Sta/Elev= 30
  4495.3 1722.61  4507.3 1723.14  4531.4 1722.85  4538.6 1722.20  4555.5 1722.65
  4560.9 1722.09  4570.9 1722.51  4579.6 1721.94  4614.5 1722.60  4633.2 1722.30
  4646.5 1722.68  4657.2 1722.38  4700.4 1722.60  4799.5 1721.79  4843.6 1720.74
  4844.1 1720.24  4851.3 1720.24  4851.8 1720.74  4853.1 1721.05  4930.9 1721.34
  5014.0 1720.94  5045.6 1721.40  5193.6 1721.36  5239.8 1721.66  5252.6 1722.22
  5300.8 1721.99  5325.0 1722.33  5330.3 1722.82  5408.1 1723.62  5443.6 1723.28
#Mann=3,-1,0
  4495.3    0.05       0  4843.6    0.04       0  4851.8    0.05       0
Bank Sta=4843.6,4851.8
Exp/Cntr=0.3,0.1

Type RM Length L Ch R = 1,23296,824,824,824
BEGIN DESCRIPTION:
Mapping XS 7a197cdb
END DESCRIPTION:
XS GIS Cut Line= 4
      1566627.14      6931868.42      1566345.05      6931981.26
      1566001.73      6932955.76      1565841.62      6932966.50
#Sta/Elev= 30
  4308.3 1726.30  4342.5 1726.66  4347.9 1725.79  4396.4 1725.60  4401.8 1724.63
  4426.0 1723.51  4431.4 1722.79  4504.1 1721.46  4509.5 1721.79  4682.5 1720.33
  4693.5 1719.78  4767.7 1719.29  4820.7 1718.34  4996.8 1717.69  4997.3 1717.19
  5004.6 1717.19  5005.1 1717.69  5017.7 1718.19  5079.6 1718.06  5110.6 1718.86
  5234.4 1720.00  5383.8 1720.55  5497.0 1722.27  5502.3 1721.89  5520.5 1722.42
  5589.9 1722.80  5626.5 1722.50  5702.2 1723.70  5742.3 1723.54  5805.8 1726.98
#Mann=3,-1,0
  4308.3    0.05       0  4996.8    0.04       0  5005.1    0.05       0
Bank Sta=4996.8,5005.1
Exp/Cntr=0.3,0.1

Type RM Length L Ch R = 1,22472,667,667,667
BEGIN DESCRIPTION:
Mapping XS a0660067
END DESCRIPTION:
XS GIS Cut Line= 3
      1566583.72      6931842.36      1565890.98      6931774.93
      1564658.37      6931504.20
#Sta/Elev= 30
  4242.0 1725.22  4361.3 1723.31  4401.5 1724.64  4431.6 1722.49  4532.1 1722.50
  4592.4 1720.65  4642.6 1721.54  4672.7 1718.76  4743.1 1720.92  4763.2 1718.16
  4883.7 1716.69  4903.8 1715.74  4913.9 1714.13  4991.9 1711.78  5046.5 1712.44
  5073.0 1711.64  5073.5 1711.14  5081.5 1711.64  5084.6 1712.81  5089.7 1711.76
  5118.2 1713.98  5138.7 1713.21  5177.3 1716.30  5182.4 1715.45  5343.4 1717.25
  5660.8 1722.19  5972.8 1722.71  6049.9 1724.86  6080.6 1724.23  6200.0 1726.04
#Mann=3,-1,0
  4242.0    0.05       0  5073.0   0.035       0  5081.5    0.05       0
Bank Sta=5073,5081.5
Exp/Cntr=0.3,0.1