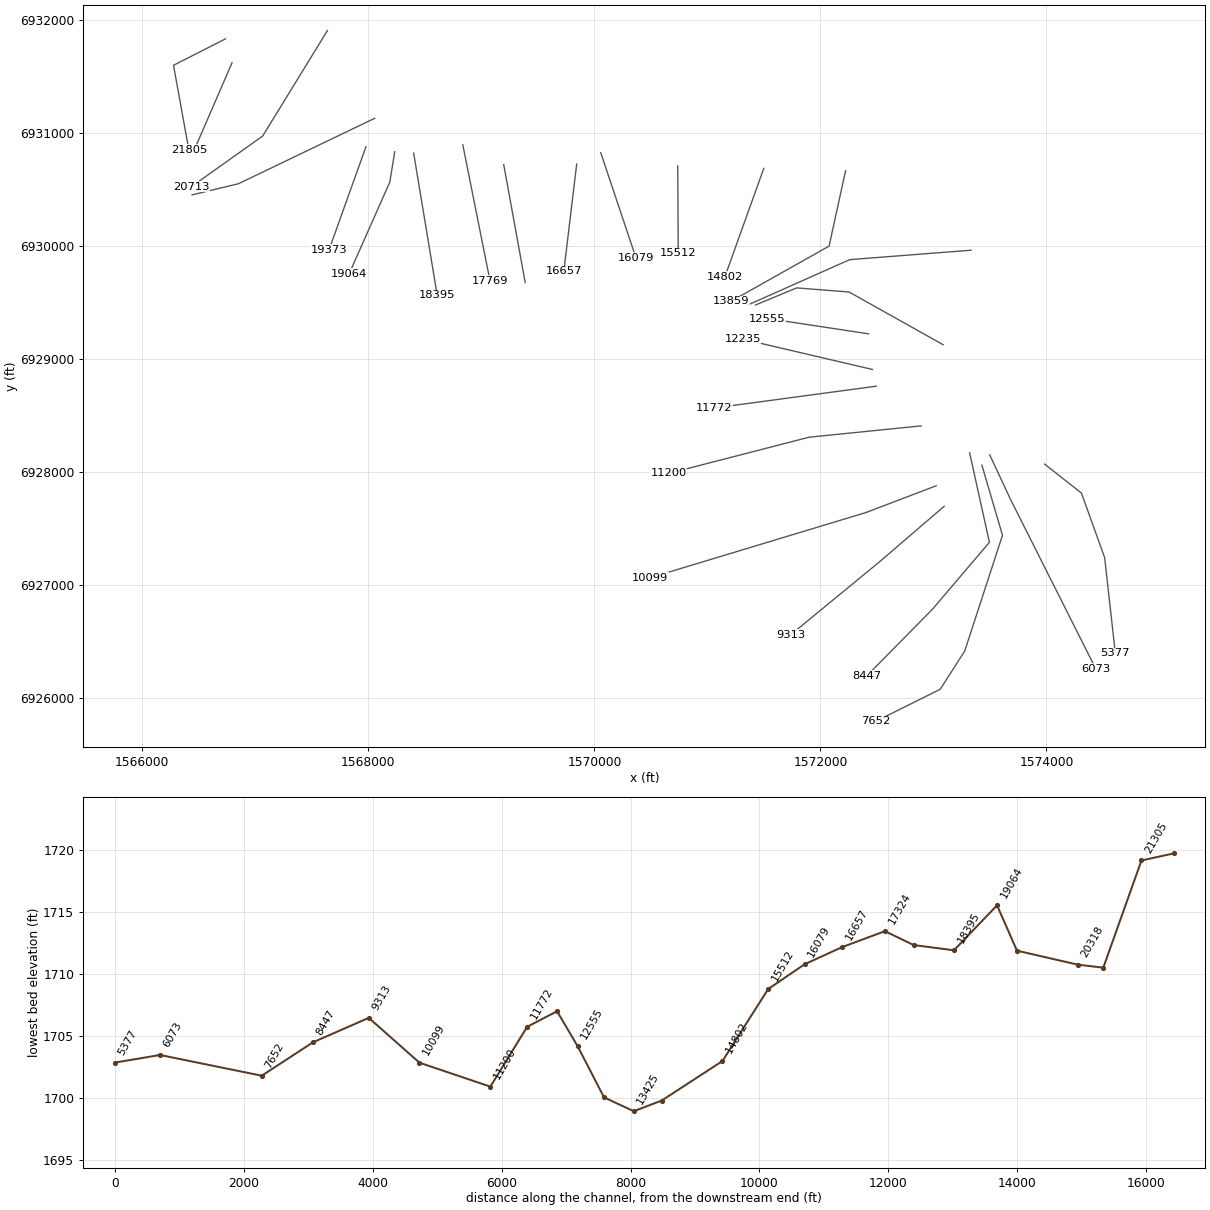
HEC-RAS study Deadman 24.prj: Deadman 24 Base Level Engineering

--- Deadman 24.g01 (geometry) --- (continued)

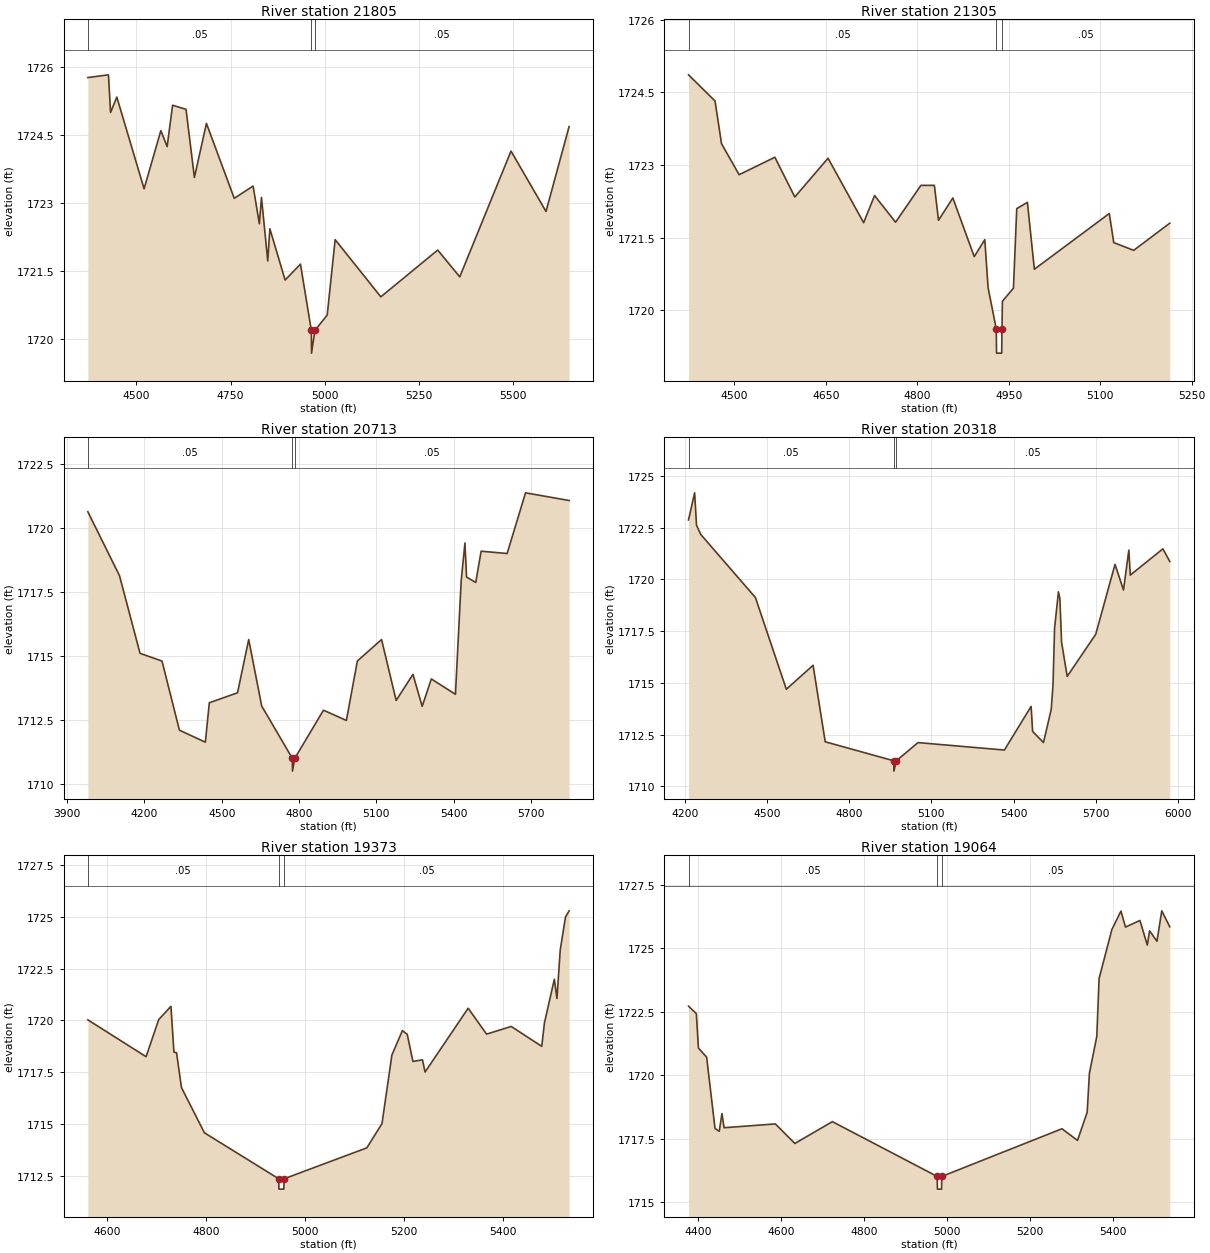
Type RM Length L Ch R = 1,21805,500,500,500
BEGIN DESCRIPTION:
Mapping XS db6137fe
END DESCRIPTION:
XS GIS Cut Line= 3
      1566735.65      6931829.34      1566275.71      6931595.78
      1566411.58      6930846.24
#Sta/Elev= 30
  4371.0 1725.76  4425.7 1725.82  4431.3 1724.99  4447.9 1725.33  4520.3 1723.31
  4564.8 1724.59  4581.5 1724.24  4596.0 1725.15  4631.6 1725.06  4653.9 1723.56
  4685.8 1724.75  4759.6 1723.10  4809.7 1723.37  4826.3 1722.54  4831.9 1723.12
  4848.6 1721.72  4854.2 1722.43  4894.7 1721.30  4935.4 1721.65  4964.3 1720.19
  4964.8 1719.69  4973.7 1720.19  5006.5 1720.53  5027.5 1722.19  5148.8 1720.93
  5299.8 1721.96  5358.3 1721.37  5494.4 1724.14  5587.3 1722.81  5648.6 1724.68
#Mann=3,-1,0
  4371.0    0.05       0  4964.3    0.05       0  4973.7    0.05       0
Bank Sta=4964.3,4973.7
Exp/Cntr=0.3,0.1

Type RM Length L Ch R = 1,21305,592,592,592
BEGIN DESCRIPTION:
Mapping XS 5b25f009
END DESCRIPTION:
XS GIS Cut Line= 2
      1566793.54      6931617.96      1566479.79      6930893.70
#Sta/Elev= 30
  4424.7 1724.86  4468.2 1724.32  4478.8 1723.44  4507.7 1722.80  4566.3 1723.16
  4599.0 1722.34  4653.5 1723.14  4711.9 1721.81  4729.8 1722.37  4764.3 1721.82
  4805.8 1722.58  4827.9 1722.58  4834.7 1721.86  4858.2 1722.32  4893.3 1721.11
  4910.6 1721.46  4916.0 1720.47  4929.4 1719.62  4929.9 1719.12  4938.3 1719.12
  4938.8 1719.62  4939.5 1720.19  4957.6 1720.46  4963.0 1722.10  4980.5 1722.23
  4991.9 1720.85  5114.8 1722.00  5122.1 1721.40  5154.8 1721.24  5214.0 1721.80
#Mann=3,-1,0
  4424.7    0.05       0  4929.4    0.05       0  4938.8    0.05       0
Bank Sta=4929.4,4938.8
Exp/Cntr=0.3,0.1

Type RM Length L Ch R = 1,20713,395,395,395
BEGIN DESCRIPTION:
Mapping XS fd585e6b
END DESCRIPTION:
XS GIS Cut Line= 3
      1567637.60      6931902.76      1567064.68      6930969.61
      1566435.63      6930522.76
#Sta/Elev= 30
  3980.8 1720.62  4103.7 1718.12  4183.2 1715.09  4268.4 1714.79  4336.0 1712.09
  4436.5 1711.62  4452.0 1713.16  4561.4 1713.55  4604.7 1715.63  4655.2 1713.03
  4773.9 1710.99  4774.4 1710.49  4783.4 1710.99  4894.7 1712.87  4983.6 1712.47
  5026.1 1714.79  5120.0 1715.63  5176.6 1713.25  5241.8 1714.27  5277.5 1713.02
  5313.1 1714.09  5406.6 1713.49  5428.8 1717.92  5443.4 1719.40  5449.7 1718.07
  5485.3 1717.86  5506.2 1719.08  5607.1 1718.99  5678.4 1721.36  5847.4 1721.06
#Mann=3,-1,0
  3980.8    0.05       0  4773.9    0.05       0  4783.4    0.05       0
Bank Sta=4773.9,4783.4
Exp/Cntr=0.3,0.1

Type RM Length L Ch R = 1,20318,945,945,945
BEGIN DESCRIPTION:
Mapping XS b7d0064b
END DESCRIPTION:
XS GIS Cut Line= 3
      1568055.12      6931126.22      1566849.39      6930547.15
      1566440.55      6930449.14
#Sta/Elev= 30
  4212.8 1722.88  4235.1 1724.19  4242.0 1722.62  4257.3 1722.18  4457.0 1719.13
  4570.1 1714.69  4667.8 1715.85  4712.1 1712.15  4962.5 1711.23  4963.0 1710.73
  4972.1 1711.23  5051.1 1712.11  5366.7 1711.75  5464.3 1713.86  5469.8 1712.65
  5509.5 1712.11  5537.7 1713.72  5544.2 1714.87  5550.0 1717.65  5564.1 1719.40
  5569.3 1719.09  5575.5 1716.97  5596.0 1715.31  5700.4 1717.35  5770.8 1720.73
  5801.7 1719.49  5821.3 1721.42  5826.5 1720.21  5945.7 1721.48  5970.8 1720.87
#Mann=3,-1,0
  4212.8    0.05       0  4962.5    0.05       0  4972.1    0.05       0
Bank Sta=4962.5,4972.1
Exp/Cntr=0.3,0.1

Type RM Length L Ch R = 1,19373,309,309,309
BEGIN DESCRIPTION:
Mapping XS db8f6418
END DESCRIPTION:
XS GIS Cut Line= 2
      1567978.82      6930875.96      1567651.35      6929961.10
#Sta/Elev= 30
  4561.1 1720.03  4678.7 1718.25  4704.1 1720.04  4728.9 1720.68  4734.9 1718.47
  4740.2 1718.44  4750.1 1716.76  4796.4 1714.58  4946.4 1712.36  4946.9 1711.86
  4956.9 1711.86  4957.4 1712.36  5124.3 1713.85  5155.0 1715.02  5175.0 1718.33
  5196.2 1719.51  5206.0 1719.33  5217.5 1718.02  5236.7 1718.10  5242.0 1717.51
  5329.0 1720.59  5366.2 1719.34  5416.0 1719.71  5477.6 1718.75  5483.0 1719.88
  5503.0 1721.99  5508.3 1721.06  5514.9 1723.40  5525.5 1724.99  5532.8 1725.29
#Mann=3,-1,0
  4561.1    0.05       0  4946.4    0.05       0  4957.4    0.05       0
Bank Sta=4946.4,4957.4
Exp/Cntr=0.3,0.1

Type RM Length L Ch R = 1,19064,669,669,669
BEGIN DESCRIPTION:
Mapping XS 47dd996d
END DESCRIPTION:
XS GIS Cut Line= 3
      1568233.07      6930831.12      1568189.67      6930561.99
      1567829.42      6929750.35
#Sta/Elev= 30
  4376.8 1722.72  4395.6 1722.43  4400.7 1721.07  4420.5 1720.71  4440.7 1717.90
  4450.9 1717.79  4457.4 1718.49  4462.5 1717.93  4586.1 1718.08  4633.2 1717.31
  4723.7 1718.17  4976.5 1716.01  4977.0 1715.51  4987.0 1715.51  4987.5 1716.01
  5277.4 1717.89  5314.9 1717.43  5338.2 1718.54  5343.6 1720.08  5361.4 1721.53
  5366.9 1723.81  5397.7 1725.74  5419.6 1726.47  5430.6 1725.84  5465.4 1726.10
  5483.2 1725.13  5488.7 1725.69  5506.5 1725.28  5518.1 1726.48  5537.4 1725.85
#Mann=3,-1,0
  4376.8    0.05       0  4976.5    0.05       0  4987.5    0.05       0
Bank Sta=4976.5,4987.5
Exp/Cntr=0.3,0.1

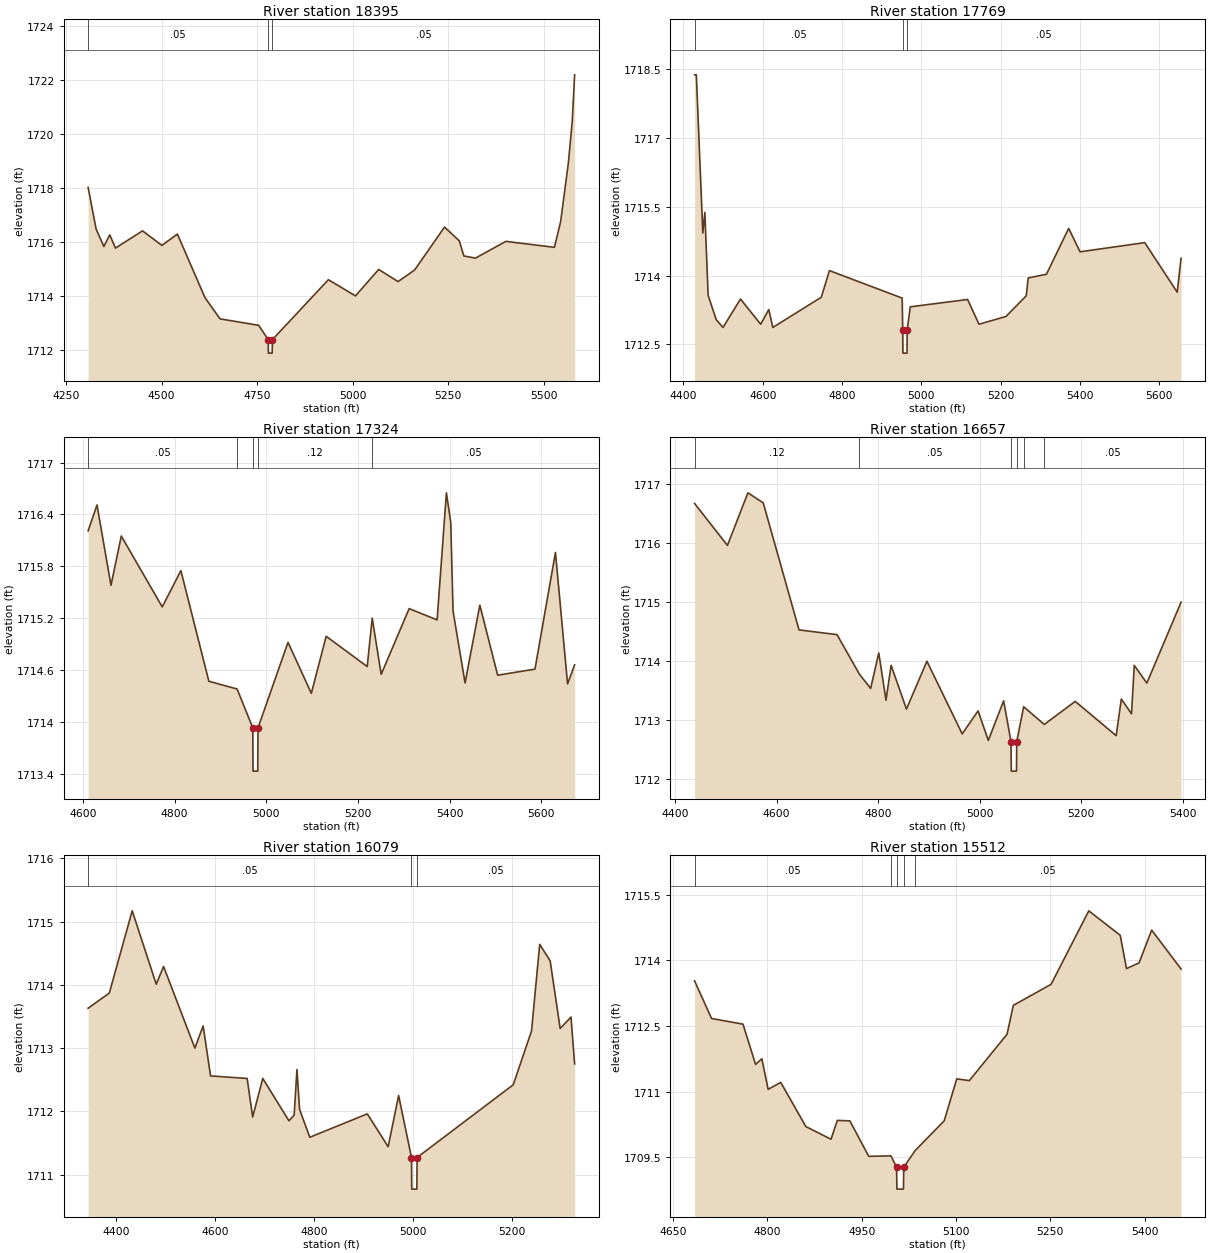
Type RM Length L Ch R = 1,18395,626,626,626
BEGIN DESCRIPTION:
Mapping XS 84ce15de
END DESCRIPTION:
XS GIS Cut Line= 2
      1568400.68      6930818.61      1568608.83      6929561.93
#Sta/Elev= 30
  4307.5 1718.03  4328.4 1716.49  4348.7 1715.84  4364.2 1716.27  4379.1 1715.78
  4450.0 1716.42  4500.7 1715.88  4541.3 1716.30  4613.3 1713.95  4652.8 1713.16
  4754.1 1712.92  4779.0 1712.39  4779.5 1711.89  4789.5 1711.89  4790.0 1712.39
  4936.6 1714.61  5007.5 1714.01  5068.3 1714.99  5119.0 1714.54  5162.4 1714.97
  5240.7 1716.56  5279.3 1716.05  5291.3 1715.49  5321.7 1715.41  5401.3 1716.03
  5528.4 1715.81  5544.7 1716.76  5565.0 1718.94  5575.2 1720.51  5581.3 1722.20
#Mann=3,-1,0
  4307.5    0.05       0  4779.0    0.05       0  4790.0    0.05       0
Bank Sta=4779,4790
Exp/Cntr=0.3,0.1

Type RM Length L Ch R = 1,17769,445,445,445
BEGIN DESCRIPTION:
Mapping XS 164de44c
END DESCRIPTION:
XS GIS Cut Line= 3
      1568835.57      6930891.57      1569067.35      6929732.69
      1569077.76      6929688.43
#Sta/Elev= 30
  4428.1 1718.38  4432.5 1718.38  4448.9 1714.93  4454.0 1715.38  4462.3 1713.57
  4482.7 1713.04  4499.8 1712.87  4543.9 1713.49  4594.9 1712.94  4615.3 1713.26
  4625.5 1712.87  4747.9 1713.53  4768.3 1714.11  4951.8 1713.51  4953.2 1712.81
  4953.7 1712.31  4963.9 1712.31  4964.4 1712.81  4972.2 1713.32  5116.8 1713.48
  5145.6 1712.94  5213.7 1713.11  5264.7 1713.56  5269.8 1713.95  5315.7 1714.03
  5371.8 1715.03  5400.6 1714.52  5563.7 1714.72  5645.6 1713.64  5655.4 1714.38
#Mann=3,-1,0
  4428.1    0.05       0  4953.2    0.05       0  4964.4    0.05       0
Bank Sta=4953.2,4964.4
Exp/Cntr=0.3,0.1

Type RM Length L Ch R = 1,17324,667,667,667
BEGIN DESCRIPTION:
Mapping XS f9e88347
END DESCRIPTION:
XS GIS Cut Line= 2
      1569197.55      6930717.09      1569387.65      6929672.86
#Sta/Elev= 30
  4611.2 1716.21  4630.6 1716.51  4661.1 1715.58  4683.6 1716.15  4772.9 1715.33
  4813.6 1715.75  4874.6 1714.47  4936.3 1714.38  4970.5 1713.93  4971.0 1713.43
  4981.3 1713.43  4981.8 1713.93  5047.3 1714.92  5098.2 1714.33  5130.6 1714.99
  5220.1 1714.64  5231.0 1715.20  5250.6 1714.55  5311.6 1715.31  5372.6 1715.18
  5392.9 1716.65  5402.3 1716.31  5407.4 1715.28  5433.6 1714.45  5465.8 1715.35
  5504.7 1714.54  5586.1 1714.61  5630.8 1715.96  5657.2 1714.44  5672.6 1714.66
#Mann=5,-1,0
  4611.2    0.05       0  4936.3    0.12       0  4970.5    0.07       0
  4981.8    0.12       0  5231.0    0.05       0
Bank Sta=4970.5,4981.8
Exp/Cntr=0.3,0.1

Type RM Length L Ch R = 1,16657,578,578,578
BEGIN DESCRIPTION:
Mapping XS f796826b
END DESCRIPTION:
XS GIS Cut Line= 2
      1569843.39      6930722.24      1569729.04      6929771.09
#Sta/Elev= 30
  4438.6 1716.67  4503.3 1715.96  4543.6 1716.85  4573.8 1716.68  4644.3 1714.53
  4719.1 1714.45  4763.2 1713.78  4785.3 1713.54  4801.3 1714.14  4815.5 1713.34
  4825.6 1713.93  4855.8 1713.19  4896.1 1714.00  4965.6 1712.77  4996.8 1713.16
  5017.0 1712.66  5047.2 1713.33  5061.7 1712.64  5062.2 1712.14  5072.5 1712.14
  5073.0 1712.64  5086.6 1713.23  5127.2 1712.93  5188.2 1713.32  5268.8 1712.74
  5278.9 1713.36  5299.0 1713.11  5304.4 1713.93  5329.2 1713.63  5396.6 1715.00
#Mann=6,-1,0
  4438.6    0.12       0  4763.2    0.05       0  5061.7    0.05       0
  5073.0    0.05       0  5086.6    0.12       0  5127.2    0.05       0
Bank Sta=5061.7,5073
Exp/Cntr=0.3,0.1

Type RM Length L Ch R = 1,16079,567,567,567
BEGIN DESCRIPTION:
Mapping XS 278adc6f
END DESCRIPTION:
XS GIS Cut Line= 2
      1570055.99      6930822.38      1570367.86      6929891.11
#Sta/Elev= 30
  4343.7 1713.63  4386.5 1713.87  4432.7 1715.17  4481.2 1714.01  4496.0 1714.29
  4559.2 1713.00  4575.9 1713.35  4590.9 1712.56  4664.7 1712.52  4675.9 1711.91
  4696.3 1712.52  4749.1 1711.85  4759.6 1711.94  4765.3 1712.66  4770.6 1712.03
  4791.2 1711.59  4907.3 1711.96  4949.4 1711.44  4970.5 1712.25  4996.5 1711.27
  4997.0 1710.77  5007.3 1710.77  5007.8 1711.27  5201.9 1712.42  5238.8 1713.27
  5255.3 1714.64  5276.4 1714.38  5296.6 1713.31  5318.5 1713.49  5325.8 1712.75
#Mann=3,-1,0
  4343.7    0.05       0  4996.5    0.05       0  5007.8    0.05       0
Bank Sta=4996.5,5007.8
Exp/Cntr=0.3,0.1

Type RM Length L Ch R = 1,15512,710,710,710
BEGIN DESCRIPTION:
Mapping XS f401a537
END DESCRIPTION:
XS GIS Cut Line= 2
      1570737.31      6930705.02      1570741.69      6929931.24
#Sta/Elev= 30
  4684.3 1713.53  4711.3 1712.67  4761.3 1712.54  4781.3 1711.62  4791.3 1711.75
  4801.3 1711.05  4821.3 1711.21  4861.3 1710.20  4901.3 1709.91  4911.3 1710.34
  4931.3 1710.33  4961.3 1709.52  4996.7 1709.53  5005.6 1709.27  5006.1 1708.77
  5016.5 1708.77  5017.0 1709.27  5035.0 1709.65  5081.3 1710.33  5101.3 1711.29
  5121.3 1711.25  5181.3 1712.31  5191.3 1712.97  5251.3 1713.45  5311.3 1715.13
  5361.3 1714.57  5371.3 1713.81  5391.3 1713.94  5411.3 1714.69  5458.1 1713.80
#Mann=5,-1,0
  4684.3    0.05       0  4996.7    0.12       0  5005.6    0.07       0
  5017.0    0.12       0  5035.0    0.05       0
Bank Sta=5005.6,5017
Exp/Cntr=0.3,0.1

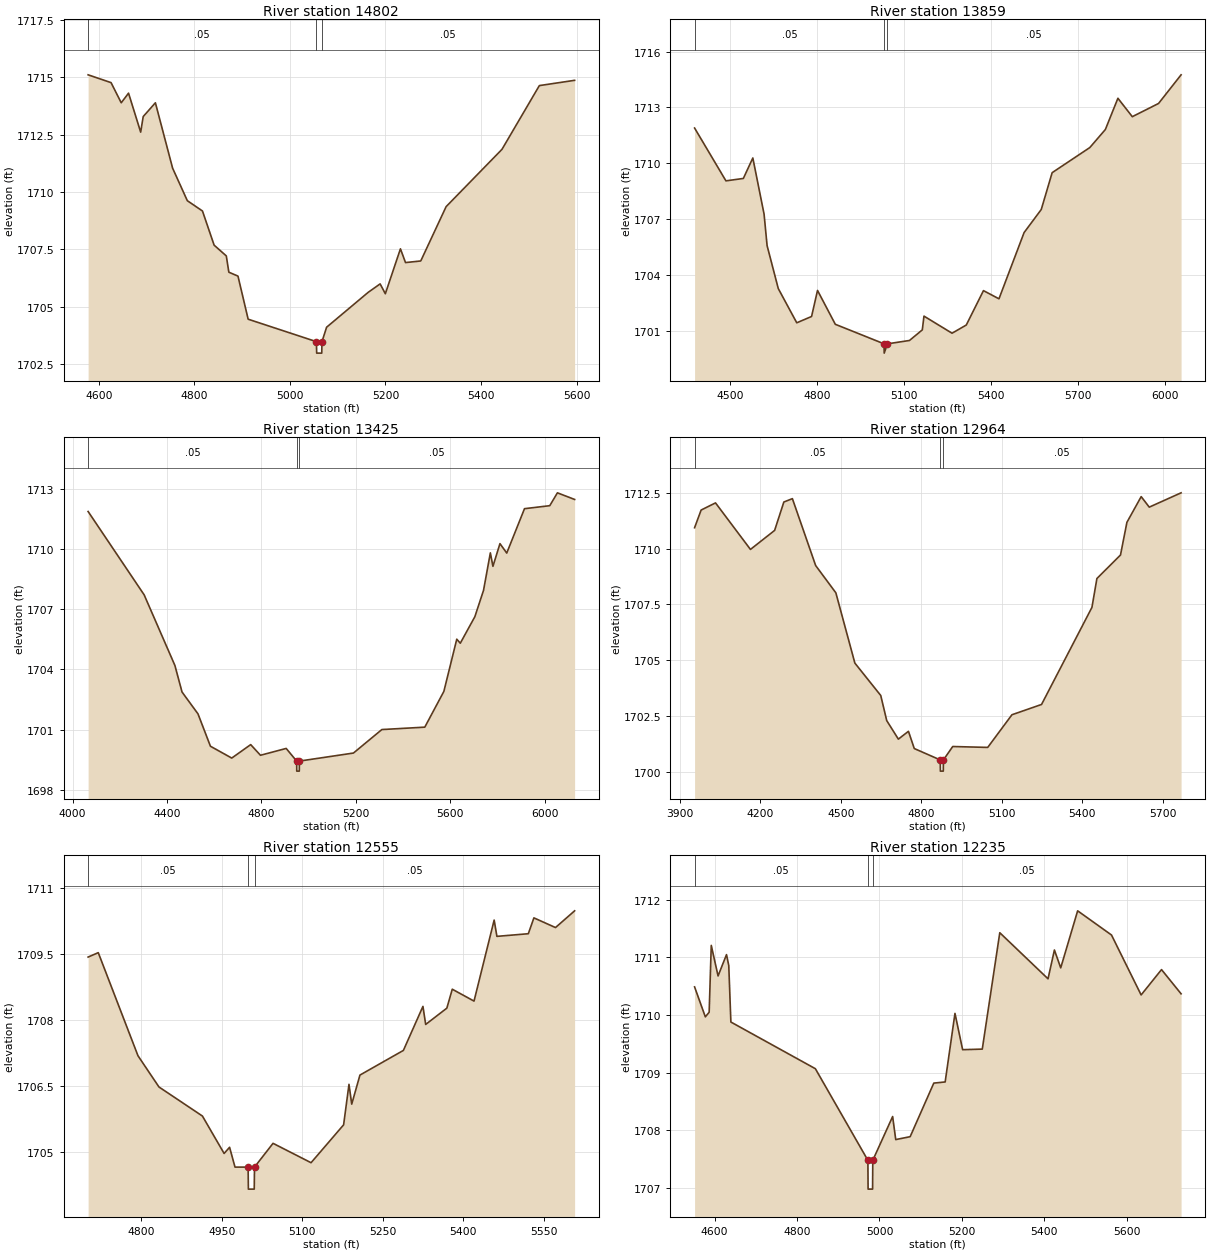
Type RM Length L Ch R = 1,14802,943,943,943
BEGIN DESCRIPTION:
Mapping XS 0310fcb8
END DESCRIPTION:
XS GIS Cut Line= 2
      1571498.34      6930683.21      1571154.60      6929724.90
#Sta/Elev= 30
  4577.7 1715.11  4625.7 1714.77  4647.0 1713.89  4662.3 1714.31  4687.7 1712.61
  4693.0 1713.29  4718.5 1713.89  4754.5 1711.04  4785.3 1709.62  4817.0 1709.17
  4841.4 1707.68  4866.9 1707.21  4872.2 1706.50  4891.3 1706.33  4912.6 1704.45
  5055.5 1703.47  5056.0 1702.97  5066.6 1702.97  5067.1 1703.47  5076.8 1704.10
  5163.7 1705.62  5188.8 1705.99  5199.7 1705.56  5231.3 1707.52  5241.9 1706.92
  5273.8 1706.99  5326.9 1709.36  5443.8 1711.86  5522.0 1714.64  5595.8 1714.87
#Mann=3,-1,0
  4577.7    0.05       0  5055.5    0.05       0  5067.1    0.05       0
Bank Sta=5055.5,5067.1
Exp/Cntr=0.3,0.1

Type RM Length L Ch R = 1,13859,434,434,434
BEGIN DESCRIPTION:
Mapping XS d25872e6
END DESCRIPTION:
XS GIS Cut Line= 3
      1572222.30      6930662.41      1572076.46      6929995.71
      1571208.31      6929507.05
#Sta/Elev= 30
  4377.5 1711.89  4485.7 1709.05  4545.8 1709.18  4578.5 1710.28  4617.3 1707.26
  4627.7 1705.57  4666.3 1703.26  4730.1 1701.42  4781.2 1701.76  4801.7 1703.16
  4863.1 1701.34  5031.3 1700.29  5031.8 1699.79  5043.0 1700.29  5119.0 1700.47
  5163.3 1701.04  5169.0 1701.78  5265.9 1700.86  5315.0 1701.30  5374.3 1703.15
  5427.8 1702.71  5514.5 1706.27  5573.7 1707.51  5611.3 1709.49  5741.3 1710.84
  5794.9 1711.81  5838.2 1713.49  5887.9 1712.50  5978.4 1713.21  6056.2 1714.75
#Mann=3,-1,0
  4377.5    0.05       0  5031.3    0.03       0  5043.0    0.05       0
Bank Sta=5031.3,5043
Exp/Cntr=0.3,0.1

Type RM Length L Ch R = 1,13425,461,461,461
BEGIN DESCRIPTION:
Mapping XS 70f4f2c9
END DESCRIPTION:
XS GIS Cut Line= 3
      1573331.69      6929959.25      1572258.76      6929875.92
      1571358.84      6929475.38
#Sta/Elev= 30
  4065.9 1711.86  4303.3 1707.71  4433.7 1704.19  4463.8 1702.87  4531.5 1701.78
  4584.1 1700.17  4674.4 1699.58  4754.7 1700.25  4796.1 1699.72  4905.1 1700.06
  4949.4 1699.43  4949.9 1698.93  4960.6 1698.93  4961.1 1699.43  5190.0 1699.83
  5310.4 1701.00  5492.3 1701.12  5573.1 1702.90  5627.8 1705.50  5642.7 1705.30
  5704.4 1706.62  5741.1 1707.93  5770.1 1709.80  5781.0 1709.13  5810.8 1710.26
  5839.5 1709.79  5914.7 1712.00  6021.8 1712.15  6054.2 1712.79  6127.1 1712.46
#Mann=3,-1,0
  4065.9    0.05       0  4949.4    0.03       0  4961.1    0.05       0
Bank Sta=4949.4,4961.1
Exp/Cntr=0.3,0.1

Type RM Length L Ch R = 1,12964,409,409,409
BEGIN DESCRIPTION:
Mapping XS bfbd0059
END DESCRIPTION:
XS GIS Cut Line= 4
      1573085.24      6929123.27      1572253.55      6929589.46
      1571790.01      6929625.92      1571425.47      6929474.89
#Sta/Elev= 30
  3955.4 1710.93  3979.8 1711.72  4033.4 1712.04  4163.6 1709.96  4253.7 1710.81
  4288.1 1712.08  4319.9 1712.23  4406.6 1709.24  4481.9 1708.02  4552.7 1704.88
  4649.2 1703.43  4671.4 1702.31  4714.8 1701.48  4752.4 1701.83  4774.1 1701.06
  4870.9 1700.55  4871.4 1700.05  4882.2 1700.05  4882.7 1700.55  4917.4 1701.15
  5047.8 1701.11  5138.1 1702.57  5248.4 1703.03  5436.2 1707.37  5454.7 1708.66
  5542.6 1709.71  5566.5 1711.17  5619.7 1712.32  5649.8 1711.85  5768.4 1712.49
#Mann=3,-1,0
  3955.4    0.05       0  4870.9    0.03       0  4882.7    0.05       0
Bank Sta=4870.9,4882.7
Exp/Cntr=0.3,0.1

Type RM Length L Ch R = 1,12555,320,320,320
BEGIN DESCRIPTION:
Mapping XS 70987704
END DESCRIPTION:
XS GIS Cut Line= 2
      1572425.39      6929219.67      1571529.77      6929355.06
#Sta/Elev= 30
  4701.4 1709.43  4720.3 1709.53  4794.2 1707.19  4833.3 1706.48  4914.2 1705.82
  4954.6 1704.97  4964.8 1705.11  4974.9 1704.66  4999.3 1704.66  4999.8 1704.16
  5010.7 1704.16  5011.2 1704.66  5045.7 1705.20  5116.5 1704.76  5177.1 1705.62
  5187.1 1706.54  5192.2 1706.09  5207.5 1706.75  5288.4 1707.31  5324.8 1708.31
  5329.9 1707.90  5369.3 1708.27  5379.4 1708.70  5419.9 1708.43  5457.4 1710.27
  5462.5 1709.90  5521.0 1709.96  5531.4 1710.32  5571.6 1710.10  5607.2 1710.48
#Mann=3,-1,0
  4701.4    0.05       0  4999.3    0.03       0  5011.2    0.05       0
Bank Sta=4999.3,5011.2
Exp/Cntr=0.3,0.1

Type RM Length L Ch R = 1,12235,463,463,463
BEGIN DESCRIPTION:
Mapping XS 6d0db382
END DESCRIPTION:
XS GIS Cut Line= 2
      1572460.46      6928904.01      1571310.51      6929173.05
#Sta/Elev= 30
  4551.2 1710.49  4577.3 1709.97  4586.6 1710.05  4591.7 1711.21  4608.2 1710.68
  4628.7 1711.05  4634.2 1710.86  4639.3 1709.88  4844.4 1709.07  4971.9 1707.48
  4972.4 1706.98  4983.3 1706.98  4983.8 1707.48  5032.0 1708.24  5039.5 1707.84
  5074.5 1707.89  5131.9 1708.82  5159.5 1708.84  5183.3 1710.03  5201.9 1709.40
  5249.6 1709.41  5292.1 1711.43  5409.2 1710.63  5424.7 1711.13  5440.0 1710.82
  5481.1 1711.81  5563.3 1711.39  5635.2 1710.35  5684.7 1710.79  5732.2 1710.37
#Mann=3,-1,0
  4551.2    0.05       0  4971.9    0.05       0  4983.8    0.05       0
Bank Sta=4971.9,4983.8
Exp/Cntr=0.3,0.1

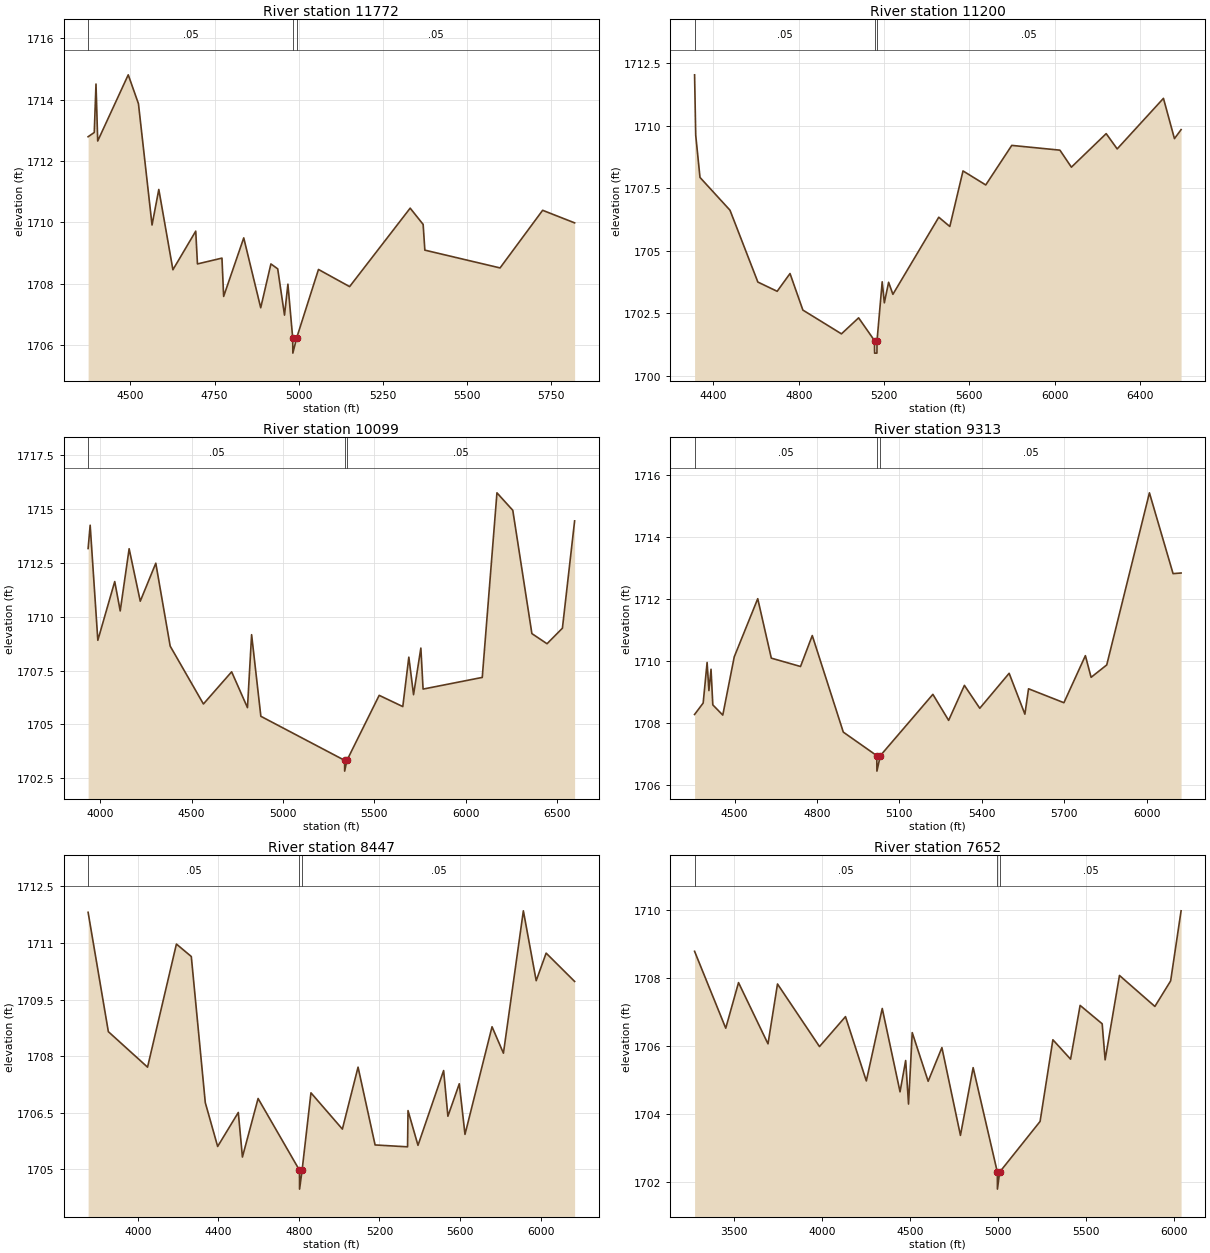
Type RM Length L Ch R = 1,11772,572,572,572
BEGIN DESCRIPTION:
Mapping XS 59ac8c5d
END DESCRIPTION:
XS GIS Cut Line= 2
      1572493.16      6928756.13      1571060.87      6928563.42
#Sta/Elev= 30
  4374.3 1712.79  4392.6 1712.93  4397.7 1714.51  4402.8 1712.65  4493.5 1714.81
  4523.8 1713.87  4564.2 1709.91  4584.3 1711.07  4626.2 1708.45  4694.0 1709.71
  4699.1 1708.64  4771.9 1708.83  4776.9 1707.58  4836.6 1709.49  4887.0 1707.21
  4917.3 1708.64  4937.5 1708.48  4957.7 1706.97  4967.8 1707.98  4982.0 1706.23
  4982.5 1705.73  4993.9 1706.23  5058.6 1708.46  5151.1 1707.90  5331.0 1710.46
  5369.5 1709.93  5374.6 1709.09  5598.0 1708.51  5724.5 1710.39  5819.5 1709.98
#Mann=3,-1,0
  4374.3    0.05       0  4982.0    0.05       0  4993.9    0.05       0
Bank Sta=4982,4993.9
Exp/Cntr=0.3,0.1

Type RM Length L Ch R = 1,11200,1101,1101,1101
BEGIN DESCRIPTION:
Mapping XS ee472faf
END DESCRIPTION:
XS GIS Cut Line= 3
      1572890.23      6928404.87      1571900.60      6928305.04
      1570654.90      6927983.85
#Sta/Elev= 30
  4311.4 1712.03  4316.7 1709.62  4336.8 1707.93  4477.5 1706.62  4608.1 1703.75
  4698.6 1703.38  4758.9 1704.09  4819.2 1702.63  5000.1 1701.68  5080.5 1702.32
  5155.0 1701.41  5155.5 1700.91  5166.4 1700.91  5166.9 1701.41  5191.1 1703.76
  5201.1 1702.92  5221.2 1703.74  5241.3 1703.26  5456.4 1706.34  5508.1 1705.97
  5570.0 1708.19  5676.6 1707.63  5798.6 1709.21  6024.4 1709.02  6078.2 1708.34
  6241.3 1709.68  6292.9 1709.07  6509.8 1711.09  6561.4 1709.48  6592.5 1709.84
#Mann=3,-1,0
  4311.4    0.05       0  5155.0    0.03       0  5166.9    0.05       0
Bank Sta=5155,5166.9
Exp/Cntr=0.3,0.1

Type RM Length L Ch R = 1,10099,786,786,786
BEGIN DESCRIPTION:
Mapping XS 39434ddb
END DESCRIPTION:
XS GIS Cut Line= 3
      1573024.76      6927875.36      1572400.96      6927637.74
      1570491.08      6927060.63
#Sta/Elev= 30
  3934.0 1713.15  3945.2 1714.23  3987.2 1708.90  4079.7 1711.62  4109.7 1710.26
  4158.5 1713.14  4219.4 1710.71  4304.4 1712.47  4383.2 1708.63  4565.1 1705.95
  4719.5 1707.44  4806.2 1705.78  4828.8 1709.16  4879.4 1705.38  5337.6 1703.34
  5338.1 1702.84  5350.6 1703.34  5527.1 1706.35  5656.3 1705.83  5689.3 1708.12
  5715.1 1706.38  5755.2 1708.54  5767.3 1706.64  6091.2 1707.18  6171.6 1715.73
  6258.3 1714.92  6362.8 1709.21  6445.7 1708.74  6529.9 1709.46  6596.7 1714.43
#Mann=3,-1,0
  3934.0    0.05       0  5337.6    0.05       0  5350.6    0.05       0
Bank Sta=5337.6,5350.6
Exp/Cntr=0.3,0.1

Type RM Length L Ch R = 1,9313,866,866,866
BEGIN DESCRIPTION:
Mapping XS f362f85e
END DESCRIPTION:
XS GIS Cut Line= 3
      1573094.17      6927693.06      1572512.58      6927193.93
      1571735.69      6926555.92
#Sta/Elev= 30
  4354.0 1708.28  4385.3 1708.65  4399.6 1709.96  4406.2 1709.05  4413.9 1709.74
  4420.4 1708.59  4456.7 1708.26  4498.4 1710.14  4584.0 1712.02  4633.4 1710.10
  4739.8 1709.83  4782.6 1710.83  4895.6 1707.71  5017.5 1706.95  5018.0 1706.45
  5030.5 1706.95  5221.8 1708.93  5279.2 1708.09  5336.6 1709.22  5392.6 1708.48
  5499.5 1709.61  5556.9 1708.29  5570.2 1709.11  5699.0 1708.66  5777.2 1710.18
  5798.0 1709.48  5854.9 1709.88  6010.4 1715.44  6096.5 1712.83  6125.7 1712.85
#Mann=3,-1,0
  4354.0    0.05       0  5017.5    0.03       0  5030.5    0.05       0
Bank Sta=5017.5,5030.5
Exp/Cntr=0.3,0.1

Type RM Length L Ch R = 1,8447,795,795,795
BEGIN DESCRIPTION:
Mapping XS b447bc82
END DESCRIPTION:
XS GIS Cut Line= 4
      1573319.87      6928166.16      1573495.06      6927374.88
      1572992.37      6926783.94      1572410.06      6926193.00
#Sta/Elev= 30
  3753.2 1711.81  3853.7 1708.65  4048.3 1707.71  4191.7 1710.97  4265.6 1710.64
  4335.1 1706.77  4396.5 1705.61  4499.0 1706.51  4519.5 1705.33  4597.3 1706.88
  4802.8 1704.98  4803.3 1704.48  4815.8 1704.98  4859.8 1707.03  5015.8 1706.07
  5093.7 1707.71  5178.3 1705.65  5339.5 1705.60  5341.8 1706.56  5391.3 1705.64
  5518.6 1707.62  5539.8 1706.41  5596.4 1707.27  5624.7 1705.93  5759.0 1708.78
  5815.6 1708.08  5914.6 1711.85  5978.3 1710.00  6027.7 1710.73  6169.1 1709.98
#Mann=3,-1,0
  3753.2    0.05       0  4802.8    0.03       0  4815.8    0.05       0
Bank Sta=4802.8,4815.8
Exp/Cntr=0.3,0.1

Type RM Length L Ch R = 1,7652,1579,1579,1579
BEGIN DESCRIPTION:
Mapping XS 00363008
END DESCRIPTION:
XS GIS Cut Line= 5
      1573428.39      6928057.61      1573610.67      6927436.99
      1573276.47      6926412.68      1573059.46      6926074.14
      1572491.89      6925792.52
#Sta/Elev= 30
  3278.0 1708.78  3454.8 1706.52  3527.3 1707.86  3694.5 1706.06  3748.4 1707.82
  3986.6 1705.98  4134.1 1706.86  4252.3 1704.97  4342.7 1707.10  4443.6 1704.65
  4475.5 1705.57  4491.8 1704.29  4512.8 1706.39  4603.1 1704.96  4681.1 1705.95
  4786.3 1703.37  4858.3 1705.36  4995.6 1702.29  4996.1 1701.79  5008.6 1702.29
  5238.1 1703.78  5310.7 1706.18  5411.0 1705.61  5465.2 1707.19  5590.3 1706.65
  5607.1 1705.59  5688.5 1708.07  5889.4 1707.16  5978.7 1707.91  6038.0 1709.97
#Mann=3,-1,0
  3278.0    0.05       0  4995.6    0.05       0  5008.6    0.05       0
Bank Sta=4995.6,5008.6
Exp/Cntr=0.3,0.1

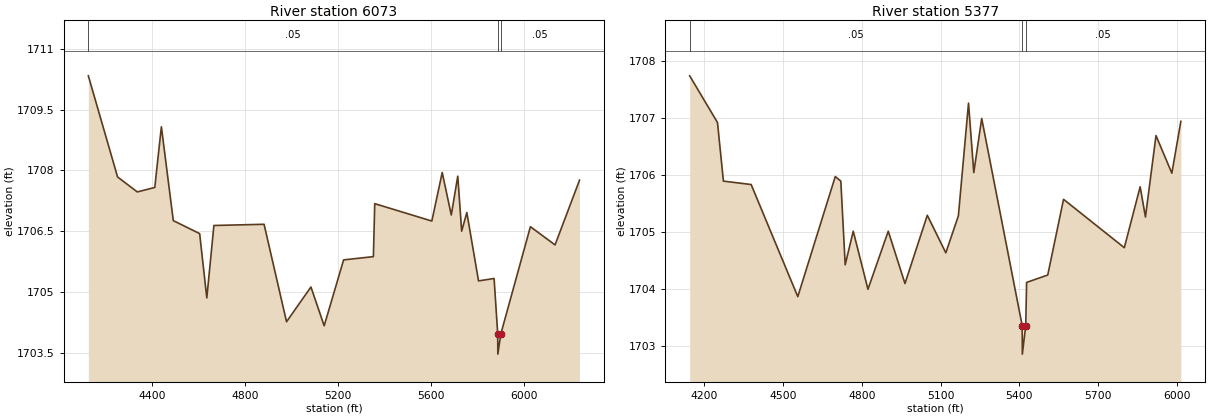
Type RM Length L Ch R = 1,6073,696,696,696
BEGIN DESCRIPTION:
Mapping XS 0653cf8d
END DESCRIPTION:
XS GIS Cut Line= 3
      1573497.81      6928148.82      1573679.93      6927758.07
      1574435.82      6926256.16
#Sta/Elev= 30
  4126.2 1710.34  4251.9 1707.84  4336.7 1707.47  4411.9 1707.58  4440.3 1709.08
  4491.6 1706.76  4604.9 1706.44  4635.7 1704.85  4666.2 1706.64  4882.0 1706.67
  4978.6 1704.26  5083.6 1705.12  5140.5 1704.16  5224.1 1705.79  5352.2 1705.87
  5358.0 1707.18  5603.5 1706.75  5648.2 1707.95  5687.2 1706.90  5715.1 1707.86
  5731.8 1706.50  5754.1 1706.96  5804.4 1705.27  5871.3 1705.33  5886.9 1703.96
  5887.4 1703.46  5900.3 1703.96  6027.5 1706.61  6133.5 1706.16  6238.7 1707.76
#Mann=3,-1,0
  4126.2    0.05       0  5886.9   0.035       0  5900.3    0.05       0
Bank Sta=5886.9,5900.3
Exp/Cntr=0.3,0.1

Type RM Length L Ch R = 1,5377,1186,1186,1186
BEGIN DESCRIPTION:
Mapping XS 345b8955
END DESCRIPTION:
XS GIS Cut Line= 4
      1573983.96      6928066.31      1574309.46      6927810.25
      1574514.58      6927239.65      1574609.09      6926393.91
#Sta/Elev= 30
  4143.9 1707.74  4249.8 1706.92  4272.4 1705.89  4378.1 1705.83  4555.8 1703.86
  4698.6 1705.97  4719.8 1705.89  4736.4 1704.42  4767.1 1705.01  4823.2 1703.99
  4900.5 1705.01  4964.2 1704.09  5049.3 1705.29  5119.8 1704.63  5167.7 1705.28
  5206.3 1707.26  5226.4 1706.04  5256.6 1706.99  5410.9 1703.35  5411.4 1702.85
  5424.3 1703.35  5427.7 1704.11  5508.2 1704.24  5568.4 1705.57  5800.0 1704.72
  5860.3 1705.79  5880.5 1705.26  5920.7 1706.69  5981.1 1706.03  6015.4 1706.94
#Mann=3,-1,0
  4143.9    0.05       0  5410.9   0.035       0  5424.3    0.05       0
Bank Sta=5410.9,5424.3
Exp/Cntr=0.3,0.1