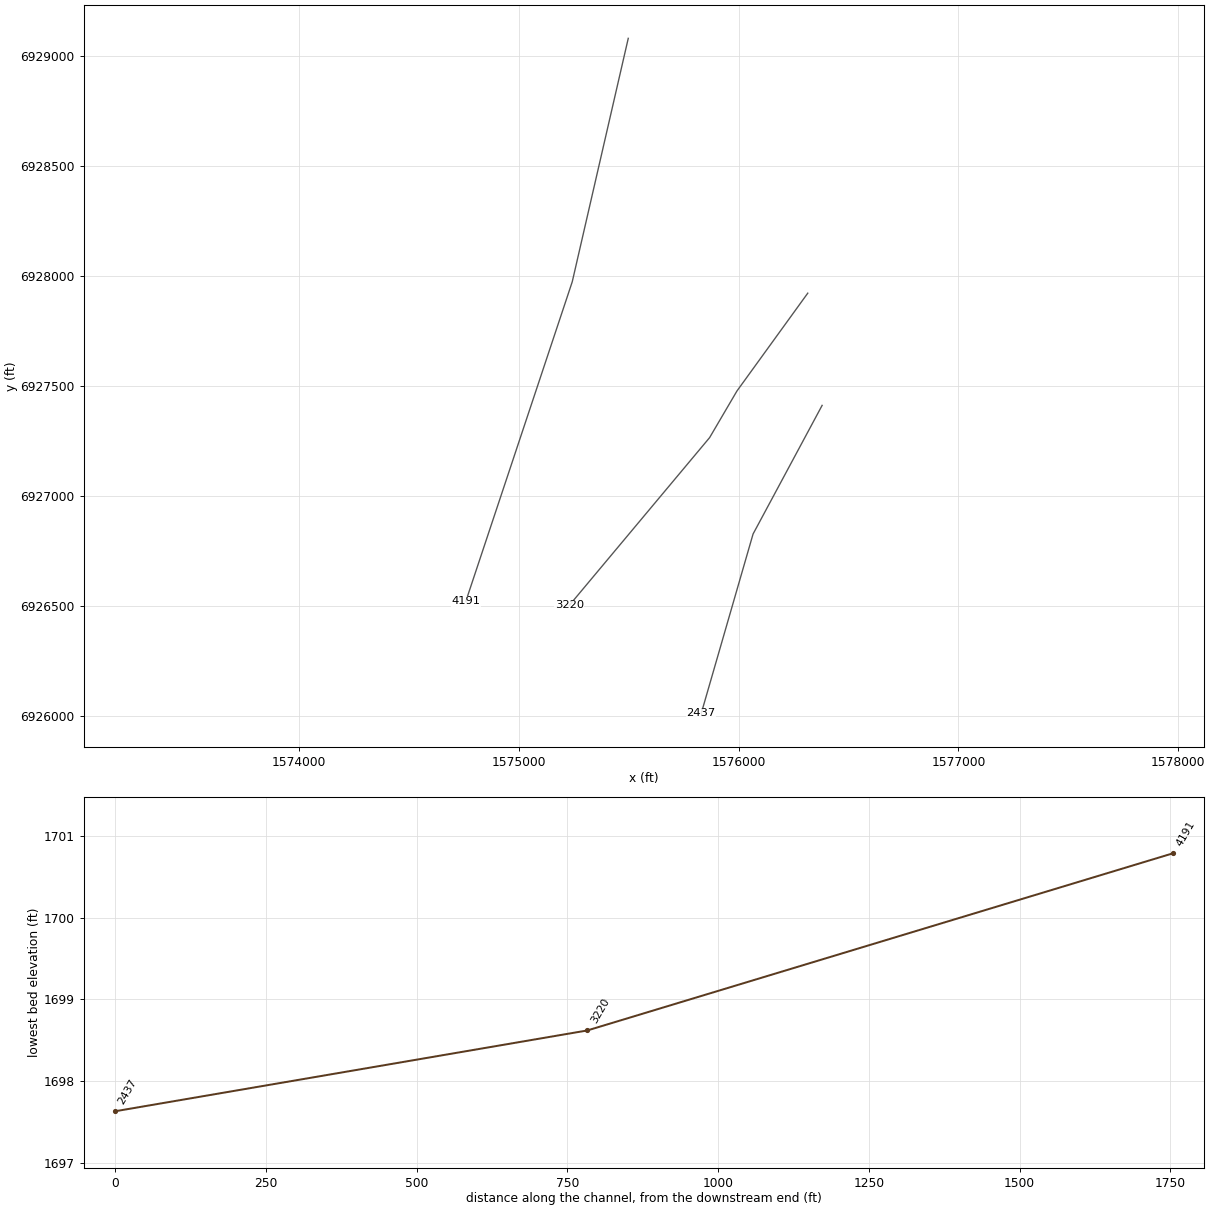
HEC-RAS study Deadman 24.prj: Deadman 24 Base Level Engineering

--- Deadman 24.g01 (geometry) --- (continued)

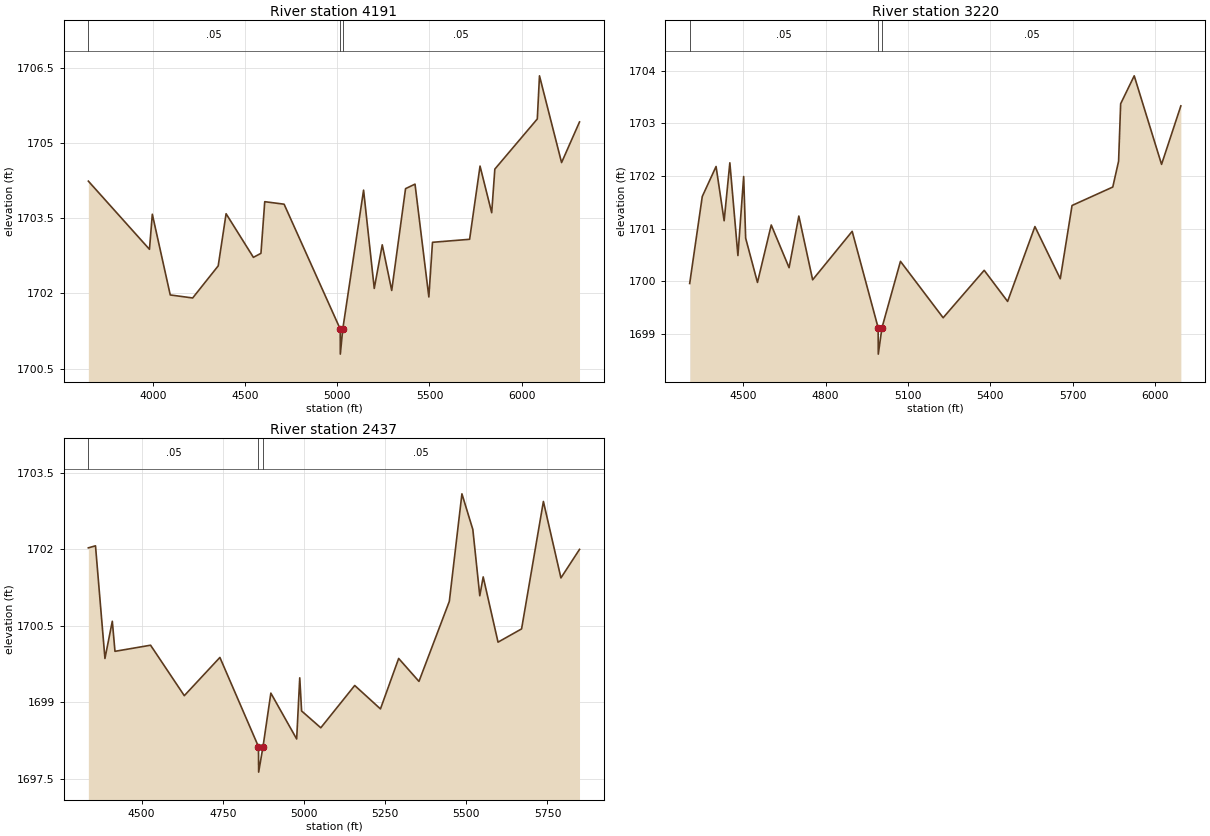
Type RM Length L Ch R = 1,4191,971,971,971
BEGIN DESCRIPTION:
Mapping XS 6b9bc825
END DESCRIPTION:
XS GIS Cut Line= 3
      1575497.97      6929081.43      1575243.13      6927974.87
      1574758.77      6926521.79
#Sta/Elev= 30
  3647.5 1704.24  3979.4 1702.88  3994.9 1703.58  4092.3 1701.97  4214.0 1701.91
  4352.7 1702.55  4395.5 1703.59  4543.8 1702.72  4584.8 1702.80  4605.4 1703.83
  4710.5 1703.78  5015.3 1701.29  5015.8 1700.79  5029.1 1701.29  5142.1 1704.06
  5200.1 1702.10  5243.5 1702.97  5294.9 1702.06  5370.0 1704.09  5421.4 1704.18
  5496.5 1701.93  5516.3 1703.02  5717.9 1703.08  5774.5 1704.54  5837.8 1703.61
  5854.9 1704.48  6085.5 1705.48  6097.3 1706.34  6217.3 1704.61  6314.7 1705.42
#Mann=3,-1,0
  3647.5    0.05       0  5015.3   0.035       0  5029.1    0.05       0
Bank Sta=5015.3,5029.1
Exp/Cntr=0.3,0.1

Type RM Length L Ch R = 1,3220,783,783,783
BEGIN DESCRIPTION:
Mapping XS 0deab356
END DESCRIPTION:
XS GIS Cut Line= 4
      1576314.68      6927923.11      1575992.49      6927478.42
      1575868.13      6927266.54      1575229.81      6926504.08
#Sta/Elev= 30
  4304.7 1699.96  4350.5 1701.61  4400.8 1702.18  4430.2 1701.15  4451.0 1702.25
  4480.4 1700.49  4501.3 1701.99  4508.6 1700.82  4551.6 1699.98  4601.8 1701.07
  4666.8 1700.26  4702.3 1701.24  4752.6 1700.03  4896.6 1700.95  4991.2 1699.12
  4991.7 1698.62  5005.1 1699.12  5072.5 1700.38  5228.0 1699.31  5377.5 1700.21
  5462.8 1699.62  5562.3 1701.04  5654.7 1700.05  5697.5 1701.44  5845.9 1701.79
  5867.1 1702.28  5874.6 1703.37  5924.0 1703.90  6023.6 1702.22  6093.9 1703.33
#Mann=3,-1,0
  4304.7    0.05       0  4991.2    0.05       0  5005.1    0.05       0
Bank Sta=4991.2,5005.1
Exp/Cntr=0.3,0.1

Type RM Length L Ch R = 1,2437,0,0,0
BEGIN DESCRIPTION:
Deadman 24 1.0
END DESCRIPTION:
XS GIS Cut Line= 3
      1576380.02      6927413.03      1576065.78      6926828.32
      1575830.01      6926013.03
#Sta/Elev= 30
  4336.2 1702.03  4358.2 1702.07  4387.3 1699.86  4410.0 1700.59  4418.2 1700.00
  4527.8 1700.12  4631.7 1699.13  4741.3 1699.88  4860.1 1698.13  4860.6 1697.63
  4874.1 1698.13  4898.2 1699.18  4977.7 1698.28  4987.2 1699.48  4992.9 1698.83
  5052.0 1698.50  5156.5 1699.33  5235.7 1698.87  5291.8 1699.86  5354.3 1699.41
  5447.8 1700.98  5486.6 1703.09  5520.2 1702.39  5541.6 1701.09  5552.1 1701.46
  5597.8 1700.18  5670.3 1700.44  5737.5 1702.94  5791.5 1701.44  5848.7 1702.00
#Mann=3,-1,0
  4336.2    0.05       0  4860.1    0.05       0  4874.1    0.05       0
Bank Sta=4860.1,4874.1
Exp/Cntr=0.3,0.1

Chan Stop Cuts=-1