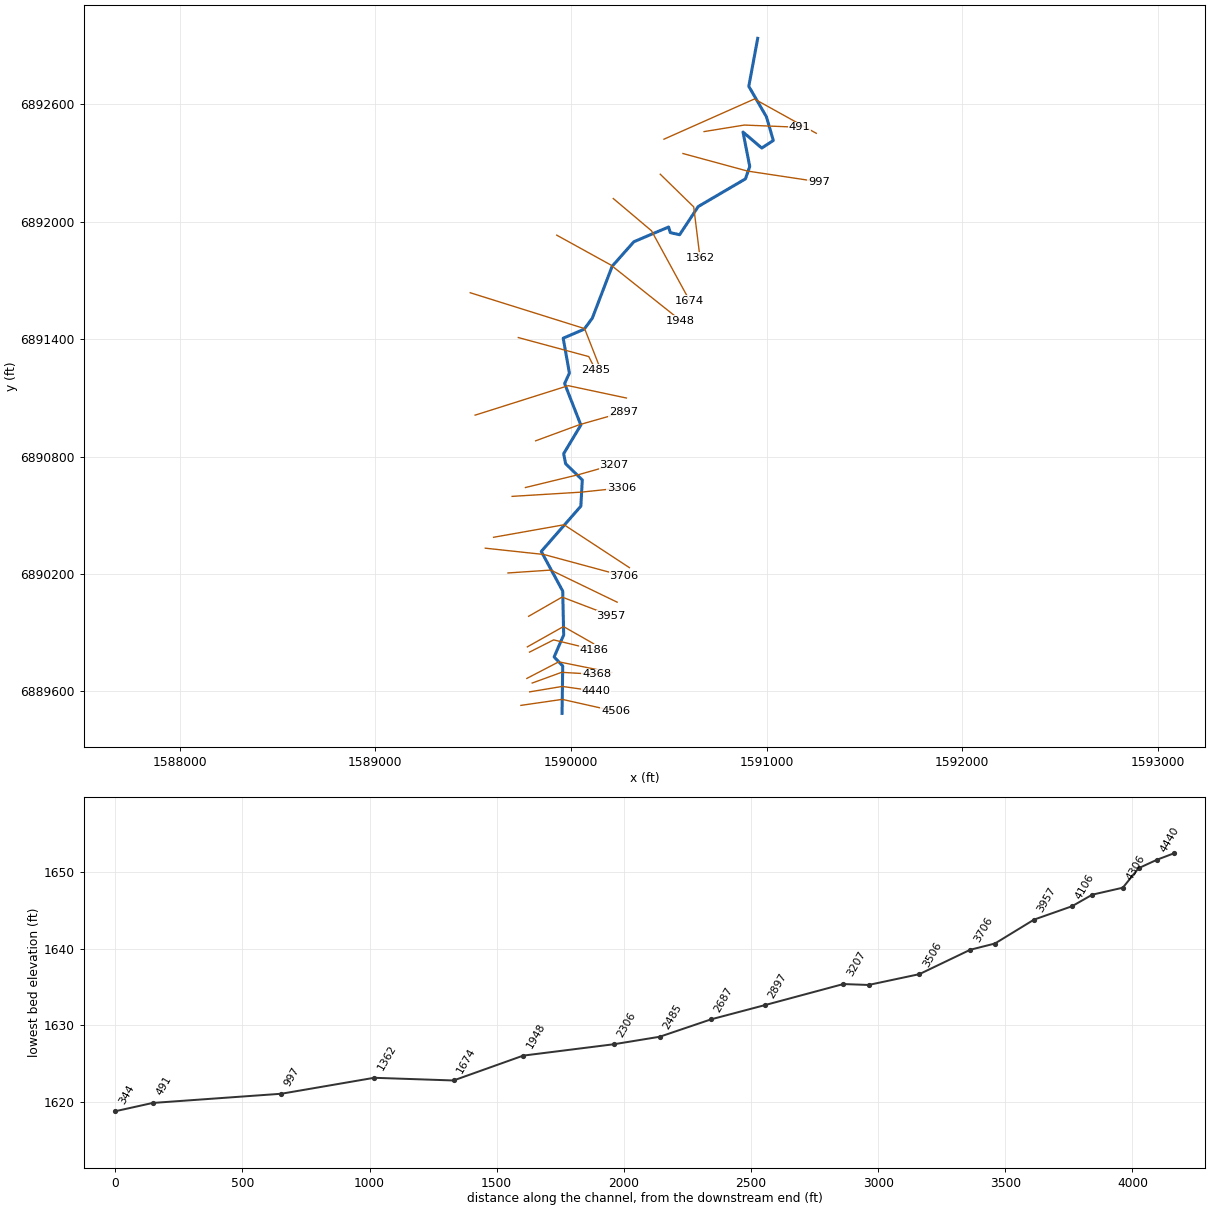
--- Deadman 25.prj (project) ---

Proj Title=Deadman 25 Base Level Engineering
Current Plan=p01
Default Exp/Contr=0.3,0.1
English Units
Geom File=g01
Flow File=f01
Plan File=p01
BEGIN DESCRIPTION:
Deadman 25
END DESCRIPTION:

--- Deadman 25.p01 (plan) ---

Plan Title=Multiple Run
Short Identifier=Multiple
Geom File=g01
Flow File=f01
Subcritical Flow
K Sum by GR= 0
Std Step Tol= 0.01
Critical Tol= 0.01
Num of Std Step Trials= 20
Max Error Tol= 0.3
Flow Tol Ratio= 0.001
Split Flow NTrial= 30
Split Flow Tol= 0.02
Split Flow Ratio= 0.02
Log Output Level= 0
Friction Slope Method= 1
Unsteady Friction Slope Method= 2
Unsteady Bridges Friction Slope Method= 1
Parabolic Critical Depth
Global Vel Dist=  1 , 1 , 1
Global Log Level= 0
CheckData=True
Encroach Param= -1, 0, 0, 0
BEGIN DESCRIPTION:
Multiple Run
END DESCRIPTION:

--- Deadman 25.f01 (steady flow) ---

Flow Title=Multiple
Number of Profiles=7
Profile Names=10-year,25-year,50-year,1pct_min,100-year,1pct_plu,500-year
River Rch & RM= Deadman 25,Reach-1,4506
      44      54      61      35      69     138      89
River Rch & RM= Deadman 25,Reach-1,997
      69      87     101      58     117     233     157
Boundary for River Rch & Prof#=Deadman 25,Reach-1,1
Up Type=0
Dn Type=3
Dn Slope=0.005
Boundary for River Rch & Prof#=Deadman 25,Reach-1,2
Up Type=0
Dn Type=3
Dn Slope=0.005
Boundary for River Rch & Prof#=Deadman 25,Reach-1,3
Up Type=0
Dn Type=3
Dn Slope=0.005
Boundary for River Rch & Prof#=Deadman 25,Reach-1,4
Up Type=0
Dn Type=3
Dn Slope=0.005
Boundary for River Rch & Prof#=Deadman 25,Reach-1,5
Up Type=0
Dn Type=3
Dn Slope=0.005
Boundary for River Rch & Prof#=Deadman 25,Reach-1,6
Up Type=0
Dn Type=3
Dn Slope=0.005
Boundary for River Rch & Prof#=Deadman 25,Reach-1,7
Up Type=0
Dn Type=3
Dn Slope=0.005

--- Deadman 25.g01 (geometry) ---

Geom Title=Existing Conditions

River Reach=Deadman 25,Reach-1
Reach XY= 30
      1589955.00      6889488.00      1589958.44      6889730.17
      1589914.55      6889776.49      1589963.32      6889888.66
      1589958.44      6890112.99      1589848.72      6890315.37
      1590051.10      6890547.01      1590058.41      6890681.12
      1589973.07      6890764.03      1589963.32      6890815.23
      1590051.10      6890961.53      1589968.20      6891173.67
      1589992.58      6891227.31      1589960.88      6891405.31
      1590068.17      6891451.64      1590109.62      6891507.72
      1590211.10      6891773.12      1590322.11      6891898.45
      1590499.38      6891973.66      1590508.33      6891945.01
      1590555.78      6891934.26      1590650.93      6892078.30
      1590892.33      6892219.72      1590914.27      6892283.12
      1590879.87      6892458.89      1590975.66      6892377.42
      1591034.75      6892415.92      1590999.62      6892536.71
      1590909.40      6892692.76      1590955.00      6892938.00

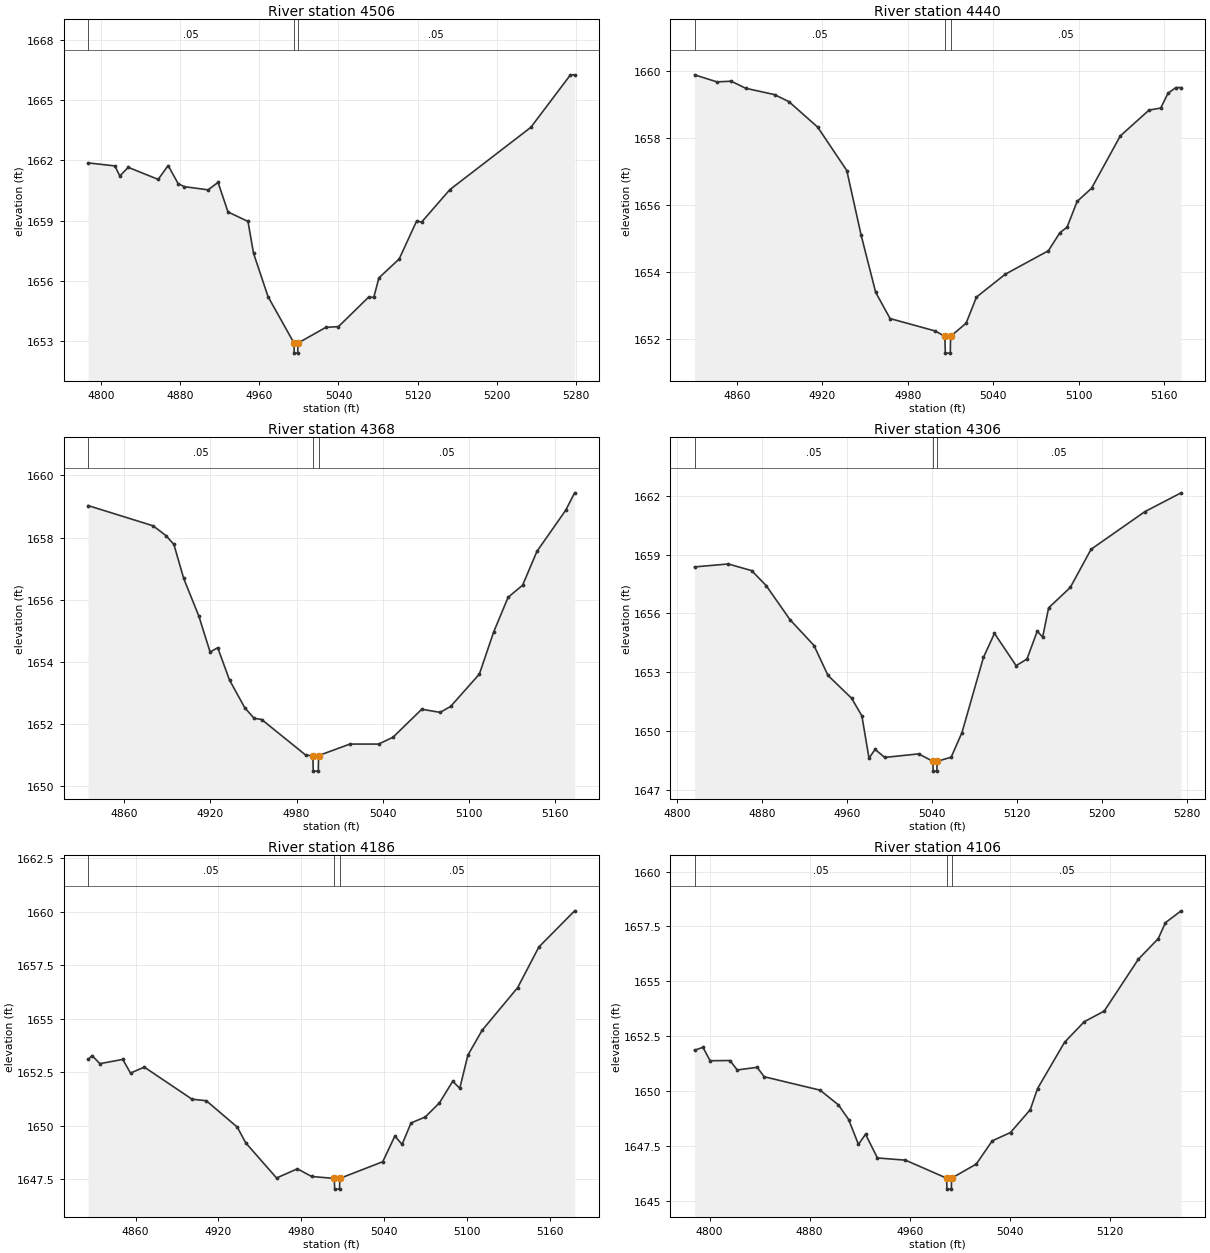
Type RM Length L Ch R = 1,4506,66,66,66
BEGIN DESCRIPTION:
Deadman 25 20.0
END DESCRIPTION:
XS GIS Cut Line= 3
      1589744.83      6889528.87      1589956.02      6889559.54
      1590228.26      6889498.52
#Sta/Elev= 30
  4786.6 1661.88  4813.7 1661.73  4818.7 1661.23  4827.2 1661.66  4857.5 1661.06
  4867.6 1661.75  4877.7 1660.85  4883.8 1660.70  4908.0 1660.54  4918.1 1660.91
  4928.2 1659.44  4948.4 1658.97  4954.0 1657.39  4968.7 1655.23  4995.0 1652.92
  4995.2 1652.42  4998.7 1652.42  4999.0 1652.92  5027.2 1653.70  5040.0 1653.74
  5070.6 1655.21  5075.7 1655.19  5080.9 1656.16  5101.4 1657.10  5119.1 1658.99
  5124.2 1658.94  5152.7 1660.55  5234.7 1663.65  5274.8 1666.26  5279.0 1666.26
#Mann=3,-1,0
  4786.6    0.05       0  4995.0    0.05       0  4999.0    0.05       0
Bank Sta=4995,4999
Exp/Cntr=0.3,0.1

Type RM Length L Ch R = 1,4440,72,72,72
BEGIN DESCRIPTION:
Mapping XS ff2c43cb
END DESCRIPTION:
XS GIS Cut Line= 3
      1589789.56      6889597.97      1589956.23      6889625.75
      1590127.24      6889601.44
#Sta/Elev= 30
  4830.3 1659.88  4846.0 1659.67  4856.0 1659.69  4866.2 1659.48  4886.5 1659.29
  4896.6 1659.08  4916.8 1658.32  4937.2 1657.03  4947.3 1655.10  4957.5 1653.40
  4967.6 1652.62  4999.3 1652.25  5006.1 1652.09  5006.4 1651.59  5009.9 1651.59
  5010.1 1652.09  5021.0 1652.48  5028.3 1653.26  5048.5 1653.94  5078.8 1654.64
  5086.9 1655.18  5091.9 1655.34  5099.0 1656.11  5109.1 1656.50  5129.3 1658.06
  5149.5 1658.83  5157.7 1658.89  5162.8 1659.33  5168.3 1659.50  5172.0 1659.50
#Mann=3,-1,0
  4830.3    0.05       0  5006.1    0.03       0  5010.1    0.05       0
Bank Sta=5006.1,5010.1
Exp/Cntr=0.3,0.1

Type RM Length L Ch R = 1,4368,62,62,62
BEGIN DESCRIPTION:
Mapping XS f80b1d83
END DESCRIPTION:
XS GIS Cut Line= 3
      1589802.54      6889643.09      1589952.76      6889697.80
      1590131.19      6889687.45
#Sta/Elev= 30
  4834.9 1659.03  4880.1 1658.38  4889.2 1658.06  4894.6 1657.78  4901.4 1656.69
  4912.0 1655.47  4919.8 1654.32  4925.1 1654.46  4933.3 1653.42  4943.9 1652.53
  4950.4 1652.19  4955.7 1652.15  4986.5 1651.00  4991.3 1650.99  4991.6 1650.49
  4995.1 1650.49  4995.3 1650.99  5017.1 1651.36  5037.1 1651.36  5047.1 1651.58
  5067.1 1652.48  5079.9 1652.38  5087.2 1652.57  5107.2 1653.61  5117.2 1654.97
  5127.2 1656.08  5137.3 1656.47  5147.3 1657.56  5167.3 1658.88  5173.5 1659.44
#Mann=3,-1,0
  4834.9    0.05       0  4991.3    0.03       0  4995.3    0.05       0
Bank Sta=4991.3,4995.3
Exp/Cntr=0.3,0.1

Type RM Length L Ch R = 1,4306,120,120,120
BEGIN DESCRIPTION:
Deadman 25 19.0
END DESCRIPTION:
XS GIS Cut Line= 3
      1589775.19      6889666.66      1589938.25      6889751.48
      1590207.30      6889697.02
#Sta/Elev= 30
  4816.2 1658.37  4847.9 1658.52  4870.0 1658.18  4883.6 1657.42  4906.2 1655.67
  4928.7 1654.36  4941.9 1652.83  4964.1 1651.67  4973.8 1650.77  4980.5 1648.61
  4986.2 1649.06  4995.3 1648.65  5027.3 1648.83  5040.7 1648.45  5040.9 1647.95
  5044.4 1647.95  5044.7 1648.45  5057.9 1648.66  5068.1 1649.92  5088.3 1653.75
  5098.7 1654.98  5119.1 1653.33  5129.3 1653.67  5139.0 1655.09  5144.1 1654.79
  5149.7 1656.28  5170.1 1657.32  5189.7 1659.27  5240.4 1661.19  5274.5 1662.15
#Mann=3,-1,0
  4816.2    0.05       0  5040.7    0.05       0  5044.7    0.05       0
Bank Sta=5040.7,5044.7
Exp/Cntr=0.3,0.1

Type RM Length L Ch R = 1,4186,80,80,80
BEGIN DESCRIPTION:
Mapping XS 7d5d664e
END DESCRIPTION:
XS GIS Cut Line= 3
      1589788.67      6889801.08      1589911.96      6889863.59
      1590120.14      6889813.28
#Sta/Elev= 30
  4825.6 1653.10  4828.5 1653.28  4834.1 1652.90  4850.7 1653.10  4856.3 1652.46
  4866.3 1652.74  4900.9 1651.24  4911.2 1651.17  4933.6 1649.94  4939.8 1649.20
  4962.1 1647.56  4977.2 1647.99  4987.5 1647.63  5003.9 1647.54  5004.2 1647.04
  5007.7 1647.04  5007.9 1647.54  5039.0 1648.32  5047.8 1649.52  5053.0 1649.13
  5059.5 1650.13  5069.8 1650.41  5080.1 1651.07  5089.7 1652.08  5094.8 1651.75
  5100.7 1653.30  5111.0 1654.46  5136.7 1656.45  5152.1 1658.35  5178.0 1660.04
#Mann=3,-1,0
  4825.6    0.05       0  5003.9    0.05       0  5007.9    0.05       0
Bank Sta=5003.9,5007.9
Exp/Cntr=0.3,0.1

Type RM Length L Ch R = 1,4106,149,149,149
BEGIN DESCRIPTION:
Deadman 25 18.0
END DESCRIPTION:
XS GIS Cut Line= 3
      1589777.57      6889827.84      1589962.38      6889931.71
      1590116.21      6889844.15
#Sta/Elev= 30
  4788.0 1651.86  4794.7 1651.99  4800.4 1651.38  4816.3 1651.39  4822.1 1650.96
  4838.0 1651.08  4843.7 1650.65  4888.3 1650.04  4903.0 1649.37  4911.2 1648.70
  4919.0 1647.57  4924.7 1648.03  4934.2 1646.95  4956.6 1646.85  4989.5 1646.03
  4989.8 1645.53  4993.3 1645.53  4993.5 1646.03  5013.2 1646.67  5026.0 1647.73
  5040.6 1648.11  5056.4 1649.15  5062.2 1650.11  5083.8 1652.22  5099.6 1653.16
  5115.5 1653.64  5142.9 1656.01  5158.7 1656.94  5164.5 1657.67  5177.0 1658.21
#Mann=3,-1,0
  4788.0    0.05       0  4989.5    0.03       0  4993.5    0.05       0
Bank Sta=4989.5,4993.5
Exp/Cntr=0.3,0.1

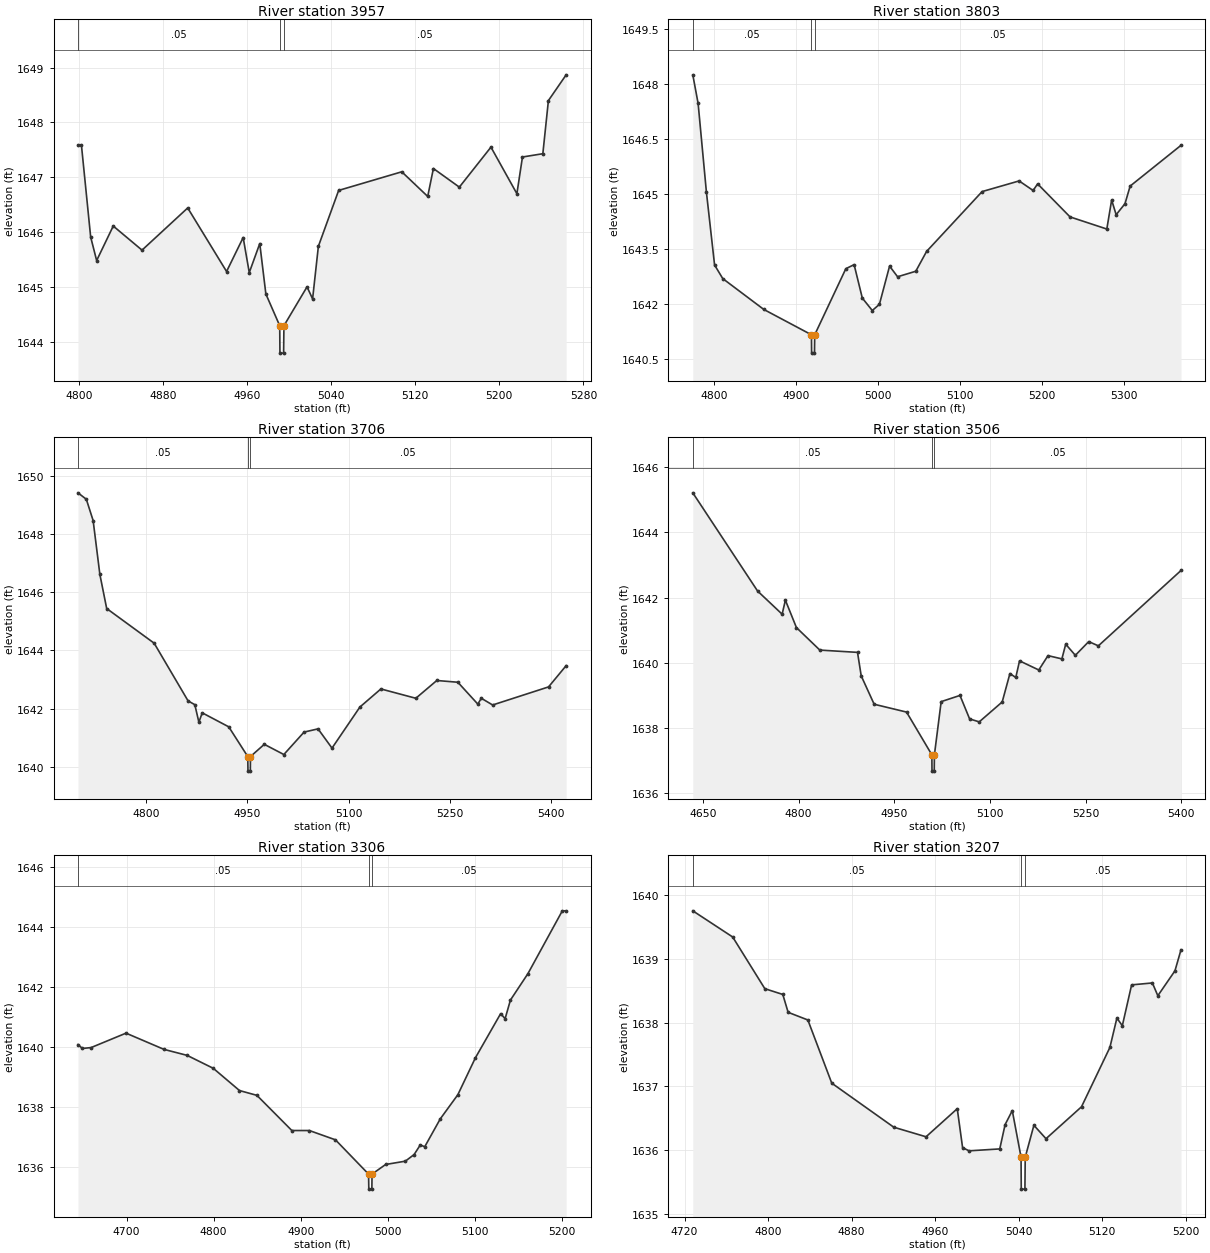
Type RM Length L Ch R = 1,3957,154,154,154
BEGIN DESCRIPTION:
Mapping XS f6aae41c
END DESCRIPTION:
XS GIS Cut Line= 3
      1589784.34      6889984.25      1589955.36      6890082.34
      1590205.39      6889986.85
#Sta/Elev= 30
  4798.8 1647.59  4802.1 1647.59  4810.9 1645.91  4816.6 1645.48  4832.4 1646.11
  4859.8 1645.67  4903.3 1646.44  4940.3 1645.28  4956.1 1645.90  4961.9 1645.26
  4971.9 1645.79  4977.7 1644.87  4990.9 1644.29  4991.1 1643.79  4994.6 1643.79
  4994.9 1644.29  5016.9 1645.00  5022.2 1644.78  5027.7 1645.74  5047.0 1646.76
  5107.1 1647.10  5131.8 1646.65  5137.2 1647.16  5161.9 1646.82  5192.0 1647.55
  5216.7 1646.70  5222.0 1647.37  5241.4 1647.43  5246.7 1648.40  5263.6 1648.87
#Mann=3,-1,0
  4798.8    0.05       0  4990.9    0.03       0  4994.9    0.05       0
Bank Sta=4990.9,4994.9
Exp/Cntr=0.3,0.1

Type RM Length L Ch R = 1,3803,97,97,97
BEGIN DESCRIPTION:
Mapping XS 902cf53a
END DESCRIPTION:
XS GIS Cut Line= 3
      1589678.48      6890205.61      1589897.20      6890220.36
      1590236.61      6890056.30
#Sta/Elev= 30
  4773.5 1648.25  4780.0 1647.47  4790.1 1645.06  4800.1 1643.07  4810.1 1642.70
  4860.2 1641.86  4918.4 1641.17  4918.6 1640.67  4922.1 1640.67  4922.4 1641.17
  4960.4 1642.97  4970.5 1643.08  4980.5 1642.17  4992.7 1641.83  5001.4 1642.00
  5013.8 1643.04  5023.6 1642.75  5045.8 1642.90  5059.0 1643.44  5126.8 1645.07
  5172.0 1645.36  5189.1 1645.10  5194.6 1645.28  5234.2 1644.38  5279.1 1644.05
  5285.0 1644.84  5290.5 1644.44  5301.3 1644.74  5307.6 1645.22  5369.7 1646.33
#Mann=3,-1,0
  4773.5    0.05       0  4918.4    0.03       0  4922.4    0.05       0
Bank Sta=4918.4,4922.4
Exp/Cntr=0.3,0.1

Type RM Length L Ch R = 1,3706,200,200,200
BEGIN DESCRIPTION:
Deadman 25 16.0
END DESCRIPTION:
XS GIS Cut Line= 3
      1589562.66      6890332.28      1589862.13      6890300.04
      1590270.21      6890189.85
#Sta/Elev= 30
  4698.8 1649.41  4711.2 1649.19  4721.3 1648.46  4731.3 1646.61  4741.4 1645.44
  4811.8 1644.25  4862.1 1642.27  4872.1 1642.14  4878.1 1641.54  4883.1 1641.86
  4922.4 1641.38  4950.6 1640.36  4950.9 1639.86  4954.4 1639.86  4954.6 1640.36
  4975.1 1640.78  5004.1 1640.43  5034.1 1641.20  5054.8 1641.31  5075.5 1640.65
  5116.9 1642.06  5148.0 1642.68  5199.8 1642.36  5230.9 1642.97  5262.1 1642.91
  5291.7 1642.16  5296.9 1642.36  5313.7 1642.13  5396.6 1642.75  5422.7 1643.48
#Mann=3,-1,0
  4698.8    0.05       0  4950.6    0.03       0  4954.6    0.05       0
Bank Sta=4950.6,4954.6
Exp/Cntr=0.3,0.1

Type RM Length L Ch R = 1,3506,200,200,200
BEGIN DESCRIPTION:
Deadman 25 15.0
END DESCRIPTION:
XS GIS Cut Line= 3
      1589604.99      6890388.00      1589965.26      6890451.93
      1590299.45      6890232.66
#Sta/Elev= 30
  4634.1 1645.21  4735.7 1642.20  4774.2 1641.49  4779.3 1641.92  4796.6 1641.08
  4833.3 1640.39  4892.4 1640.32  4898.2 1639.60  4918.5 1638.73  4969.3 1638.49
  5009.0 1637.18  5009.2 1636.68  5012.7 1636.68  5013.0 1637.18  5023.6 1638.81
  5053.1 1639.00  5068.2 1638.28  5083.3 1638.19  5119.3 1638.80  5131.4 1639.67
  5140.6 1639.55  5146.5 1640.06  5176.7 1639.78  5191.1 1640.22  5212.9 1640.12
  5218.9 1640.57  5234.0 1640.23  5255.0 1640.65  5270.1 1640.52  5399.7 1642.83
#Mann=3,-1,0
  4634.1    0.05       0  5009.0    0.03       0  5013.0    0.05       0
Bank Sta=5009,5013
Exp/Cntr=0.3,0.1

Type RM Length L Ch R = 1,3306,99,99,99
BEGIN DESCRIPTION:
Deadman 25 14.0
END DESCRIPTION:
XS GIS Cut Line= 3
      1589699.88      6890597.05      1590055.01      6890618.81
      1590258.66      6890640.56
#Sta/Elev= 30
  4644.2 1640.08  4649.3 1639.95  4659.3 1639.98  4699.4 1640.46  4743.0 1639.92
  4769.6 1639.72  4799.6 1639.29  4829.7 1638.55  4849.7 1638.39  4889.8 1637.22
  4909.9 1637.22  4939.9 1636.91  4977.9 1635.77  4978.2 1635.27  4981.7 1635.27
  4981.9 1635.77  4997.5 1636.09  5020.1 1636.20  5030.2 1636.42  5037.3 1636.74
  5042.4 1636.68  5060.3 1637.61  5080.4 1638.41  5100.6 1639.64  5129.6 1641.11
  5134.7 1640.94  5140.8 1641.56  5160.9 1642.44  5200.4 1644.53  5204.8 1644.53
#Mann=3,-1,0
  4644.2    0.05       0  4977.9    0.05       0  4981.9    0.05       0
Bank Sta=4977.9,4981.9
Exp/Cntr=0.3,0.1

Type RM Length L Ch R = 1,3207,310,310,310
BEGIN DESCRIPTION:
Mapping XS ea6c130c
END DESCRIPTION:
XS GIS Cut Line= 3
      1589767.90      6890642.25      1590043.03      6890709.08
      1590220.54      6890759.30
#Sta/Elev= 30
  4727.9 1639.75  4766.1 1639.34  4796.9 1638.53  4814.1 1638.44  4819.2 1638.16
  4838.1 1638.04  4861.0 1637.05  4920.4 1636.36  4951.3 1636.21  4981.2 1636.65
  4986.3 1636.04  4992.5 1635.99  5021.9 1636.02  5027.0 1636.40  5033.9 1636.62
  5042.3 1635.89  5042.5 1635.39  5046.0 1635.39  5046.3 1635.89  5054.6 1636.39
  5066.2 1636.18  5100.2 1636.68  5127.4 1637.61  5134.1 1638.07  5139.3 1637.95
  5148.2 1638.59  5168.1 1638.62  5173.3 1638.42  5189.7 1638.81  5195.5 1639.14
#Mann=3,-1,0
  4727.9    0.05       0  5042.3    0.05       0  5046.3    0.05       0
Bank Sta=5042.3,5046.3
Exp/Cntr=0.3,0.1

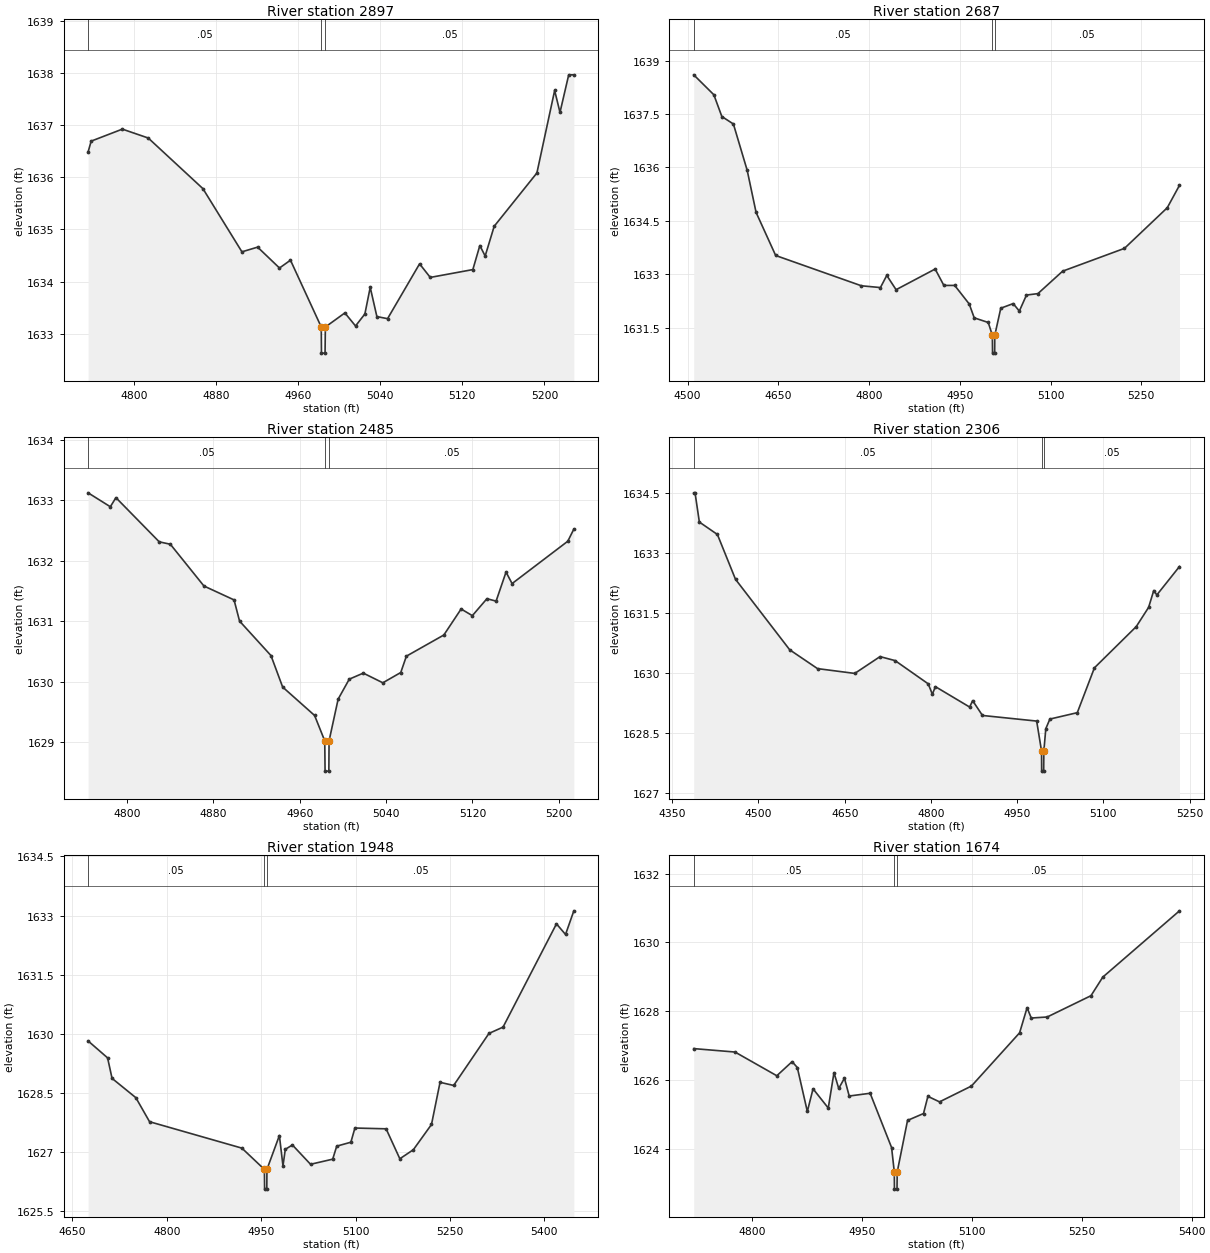
Type RM Length L Ch R = 1,2897,210,210,210
BEGIN DESCRIPTION:
Mapping XS a60b8dcf
END DESCRIPTION:
XS GIS Cut Line= 3
      1589819.96      6890880.96      1590043.90      6890963.42
      1590269.60      6891027.66
#Sta/Elev= 30
  4755.4 1636.48  4758.4 1636.69  4788.8 1636.92  4814.0 1636.75  4867.3 1635.78
  4905.3 1634.57  4920.6 1634.66  4941.9 1634.26  4952.6 1634.41  4982.6 1633.13
  4982.8 1632.63  4986.3 1632.63  4986.6 1633.13  5005.6 1633.40  5016.0 1633.15
  5025.1 1633.38  5030.3 1633.89  5036.8 1633.33  5047.2 1633.29  5078.4 1634.34
  5088.8 1634.08  5130.3 1634.23  5137.1 1634.69  5142.3 1634.49  5151.1 1635.06
  5192.7 1636.08  5210.0 1637.66  5215.2 1637.24  5223.7 1637.96  5228.7 1637.96
#Mann=3,-1,0
  4755.4    0.05       0  4982.6    0.03       0  4986.6    0.05       0
Bank Sta=4982.6,4986.6
Exp/Cntr=0.3,0.1

Type RM Length L Ch R = 1,2687,202,202,202
BEGIN DESCRIPTION:
Deadman 25 11.0
END DESCRIPTION:
XS GIS Cut Line= 3
      1589510.68      6891012.21      1589986.87      6891162.80
      1590284.01      6891099.71
#Sta/Elev= 30
  4510.0 1638.60  4543.3 1638.04  4556.5 1637.43  4575.6 1637.22  4598.4 1635.92
  4613.1 1634.74  4645.5 1633.53  4787.2 1632.68  4818.7 1632.63  4829.2 1632.97
  4844.6 1632.57  4909.2 1633.15  4923.6 1632.69  4941.5 1632.69  4965.5 1632.17
  4973.8 1631.78  4997.0 1631.65  5003.8 1631.29  5004.1 1630.79  5007.6 1630.79
  5007.8 1631.29  5017.7 1632.05  5038.2 1632.18  5048.4 1631.97  5060.2 1632.42
  5079.1 1632.46  5120.0 1633.09  5222.2 1633.73  5293.0 1634.87  5313.2 1635.50
#Mann=3,-1,0
  4510.0    0.05       0  5003.8    0.03       0  5007.8    0.05       0
Bank Sta=5003.8,5007.8
Exp/Cntr=0.3,0.1

Type RM Length L Ch R = 1,2485,179,179,179
BEGIN DESCRIPTION:
Mapping XS b4e837b5
END DESCRIPTION:
XS GIS Cut Line= 3
      1589731.42      6891408.73      1590091.65      6891311.51
      1590126.33      6891243.01
#Sta/Elev= 30
  4764.0 1633.12  4784.6 1632.89  4789.8 1633.04  4829.9 1632.31  4840.2 1632.27
  4871.3 1631.58  4899.2 1631.35  4904.3 1631.00  4933.4 1630.43  4944.2 1629.91
  4973.8 1629.44  4983.2 1629.02  4983.5 1628.52  4987.0 1628.52  4987.2 1629.02
  4995.6 1629.71  5005.9 1630.04  5018.9 1630.14  5037.0 1629.98  5053.6 1630.15
  5058.8 1630.42  5093.5 1630.77  5109.5 1631.20  5119.9 1631.09  5133.4 1631.37
  5141.9 1631.33  5151.1 1631.81  5156.7 1631.62  5208.3 1632.32  5213.9 1632.52
#Mann=3,-1,0
  4764.0    0.05       0  4983.2    0.03       0  4987.2    0.05       0
Bank Sta=4983.2,4987.2
Exp/Cntr=0.3,0.1

Type RM Length L Ch R = 1,2306,358,358,358
BEGIN DESCRIPTION:
Deadman 25 9.0
END DESCRIPTION:
XS GIS Cut Line= 3
      1589485.64      6891637.80      1590070.28      6891454.50
      1590155.01      6891237.98
#Sta/Elev= 30
  4387.3 1634.50  4389.6 1634.50  4397.1 1633.77  4428.5 1633.46  4460.0 1632.34
  4554.3 1630.58  4602.7 1630.11  4667.5 1629.99  4711.5 1630.41  4737.7 1630.31
  4795.3 1629.73  4802.5 1629.47  4807.8 1629.66  4867.4 1629.15  4872.6 1629.31
  4889.7 1628.94  4984.0 1628.80  4992.5 1628.05  4992.7 1627.55  4996.2 1627.55
  4996.5 1628.05  4999.9 1628.61  5007.0 1628.85  5054.7 1629.01  5084.5 1630.13
  5157.3 1631.16  5178.8 1631.64  5187.7 1632.06  5193.1 1631.95  5232.5 1632.66
#Mann=3,-1,0
  4387.3    0.05       0  4992.5    0.03       0  4996.5    0.05       0
Bank Sta=4992.5,4996.5
Exp/Cntr=0.3,0.1

Type RM Length L Ch R = 1,1948,274,274,274
BEGIN DESCRIPTION:
Mapping XS 17edd977
END DESCRIPTION:
XS GIS Cut Line= 3
      1589927.86      6891932.05      1590204.62      6891779.43
      1590561.37      6891495.65
#Sta/Elev= 30
  4674.9 1629.82  4705.9 1629.39  4713.0 1628.87  4750.8 1628.38  4772.6 1627.77
  4919.3 1627.10  4955.1 1626.56  4955.4 1626.06  4958.9 1626.06  4959.1 1626.56
  4978.9 1627.42  4984.6 1626.65  4988.3 1627.07  4999.6 1627.18  5028.4 1626.69
  5063.6 1626.82  5070.0 1627.15  5092.5 1627.25  5098.9 1627.61  5148.5 1627.59
  5170.3 1626.83  5191.8 1627.06  5220.6 1627.70  5234.2 1628.77  5255.8 1628.69
  5311.9 1630.01  5334.3 1630.17  5419.2 1632.79  5433.6 1632.52  5446.8 1633.12
#Mann=3,-1,0
  4674.9    0.05       0  4955.1    0.03       0  4959.1    0.05       0
Bank Sta=4955.1,4959.1
Exp/Cntr=0.3,0.1

Type RM Length L Ch R = 1,1674,312,312,312
BEGIN DESCRIPTION:
Mapping XS 0af535d5
END DESCRIPTION:
XS GIS Cut Line= 3
      1590216.84      6892119.27      1590412.19      6891954.44
      1590607.56      6891596.26
#Sta/Elev= 30
  4719.8 1626.91  4776.2 1626.81  4833.3 1626.12  4854.2 1626.53  4861.3 1626.36
  4875.0 1625.08  4882.8 1625.74  4903.6 1625.18  4911.4 1626.21  4917.9 1625.75
  4925.7 1626.05  4932.2 1625.53  4960.8 1625.61  4990.1 1624.03  4993.8 1623.32
  4994.0 1622.82  4997.5 1622.82  4997.8 1623.32  5011.9 1624.82  5033.7 1625.02
  5039.7 1625.52  5055.6 1625.36  5099.2 1625.82  5165.0 1627.37  5175.2 1628.10
  5180.9 1627.80  5202.7 1627.83  5262.5 1628.45  5278.6 1628.99  5383.4 1630.92
#Mann=3,-1,0
  4719.8    0.05       0  4993.8    0.03       0  4997.8    0.05       0
Bank Sta=4993.8,4997.8
Exp/Cntr=0.3,0.1

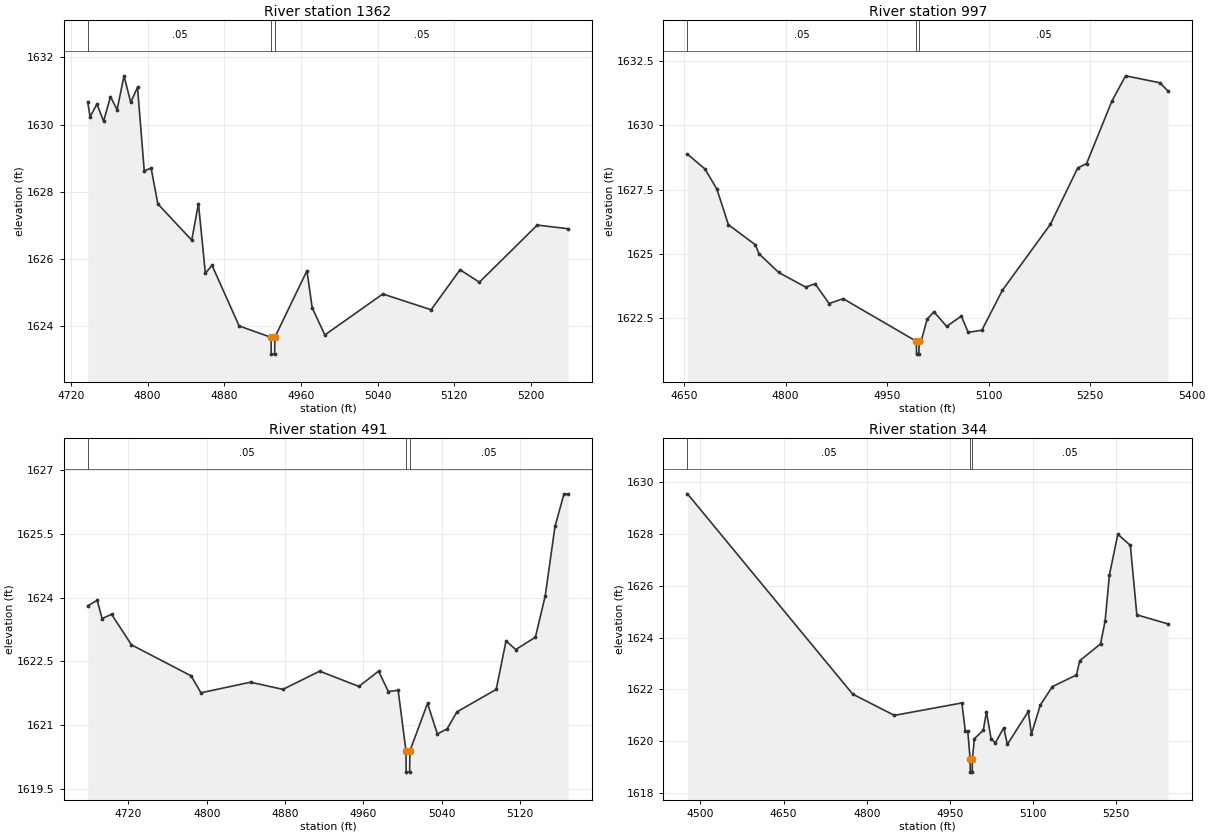
Type RM Length L Ch R = 1,1362,365,365,365
BEGIN DESCRIPTION:
Mapping XS 0df49415
END DESCRIPTION:
XS GIS Cut Line= 3
      1590456.94      6892243.44      1590627.91      6892076.55
      1590660.23      6891815.96
#Sta/Elev= 30
  4737.5 1630.68  4740.0 1630.23  4747.1 1630.61  4754.1 1630.10  4761.3 1630.83
  4768.2 1630.44  4775.4 1631.45  4782.4 1630.66  4789.5 1631.11  4796.5 1628.63
  4803.7 1628.70  4810.7 1627.64  4846.1 1626.56  4853.1 1627.65  4860.3 1625.58
  4867.3 1625.81  4895.5 1624.01  4928.8 1623.67  4929.1 1623.17  4932.6 1623.17
  4932.8 1623.67  4966.3 1625.65  4971.8 1624.55  4985.0 1623.74  5045.5 1624.96
  5095.9 1624.49  5126.1 1625.68  5146.3 1625.31  5206.7 1627.01  5239.0 1626.90
#Mann=3,-1,0
  4737.5    0.05       0  4928.8    0.03       0  4932.8    0.05       0
Bank Sta=4928.8,4932.8
Exp/Cntr=0.3,0.1

Type RM Length L Ch R = 1,997,506,506,506
BEGIN DESCRIPTION:
Mapping XS 27aeae65
END DESCRIPTION:
XS GIS Cut Line= 3
      1590572.98      6892349.24      1590902.64      6892259.70
      1591266.91      6892204.76
#Sta/Elev= 30
  4655.0 1628.88  4680.9 1628.30  4698.5 1627.52  4715.5 1626.13  4755.3 1625.35
  4760.7 1625.00  4789.9 1624.27  4829.7 1623.70  4843.6 1623.83  4864.3 1623.06
  4885.1 1623.25  4993.2 1621.59  4993.5 1621.09  4997.0 1621.09  4997.2 1621.59
  5000.3 1621.59  5009.1 1622.45  5019.2 1622.74  5038.0 1622.17  5059.7 1622.57
  5069.8 1621.94  5090.0 1622.02  5120.4 1623.58  5191.1 1626.14  5231.6 1628.34
  5244.7 1628.51  5282.2 1630.95  5302.4 1631.93  5353.0 1631.66  5365.0 1631.34
#Mann=3,-1,0
  4655.0    0.05       0  4993.2    0.05       0  4997.2    0.05       0
Bank Sta=4993.2,4997.2
Exp/Cntr=0.3,0.1

Type RM Length L Ch R = 1,491,147,147,147
BEGIN DESCRIPTION:
Mapping XS ee9911cd
END DESCRIPTION:
XS GIS Cut Line= 3
      1590680.91      6892461.37      1590886.35      6892494.80
      1591168.48      6892483.38
#Sta/Elev= 30
  4678.5 1623.81  4688.2 1623.94  4693.2 1623.51  4702.9 1623.61  4723.2 1622.89
  4784.0 1622.16  4794.1 1621.76  4844.7 1622.01  4877.8 1621.84  4915.3 1622.27
  4955.3 1621.91  4975.4 1622.27  4985.4 1621.79  4995.4 1621.82  5003.4 1620.39
  5003.6 1619.89  5007.1 1619.89  5007.4 1620.39  5025.4 1621.51  5035.4 1620.79
  5045.4 1620.91  5055.4 1621.31  5095.5 1621.84  5105.5 1622.98  5115.5 1622.78
  5135.5 1623.07  5145.5 1624.04  5155.5 1625.68  5164.7 1626.45  5169.0 1626.45
#Mann=3,-1,0
  4678.5    0.05       0  5003.4    0.03       0  5007.4    0.05       0
Bank Sta=5003.4,5007.4
Exp/Cntr=0.3,0.1

Type RM Length L Ch R = 1,344,0,0,0
BEGIN DESCRIPTION:
Deadman 25 1.0
END DESCRIPTION:
XS GIS Cut Line= 3
      1590475.87      6892422.55      1590938.27      6892628.06
      1591254.15      6892452.71
#Sta/Elev= 30
  4476.5 1629.55  4774.8 1621.82  4850.0 1621.00  4971.8 1621.48  4978.0 1620.39
  4982.5 1620.39  4986.7 1619.31  4987.0 1618.81  4990.5 1618.81  4990.7 1619.31
  4994.4 1620.10  5010.5 1620.43  5016.2 1621.14  5024.5 1620.10  5032.2 1619.94
  5047.4 1620.52  5053.9 1619.88  5091.7 1621.15  5097.4 1620.28  5113.4 1621.40
  5135.2 1622.11  5178.6 1622.56  5184.6 1623.11  5222.1 1623.76  5230.4 1624.65
  5238.1 1626.42  5253.3 1627.99  5275.9 1627.56  5287.6 1624.88  5343.8 1624.53
#Mann=3,-1,0
  4476.5    0.05       0  4986.7    0.03       0  4990.7    0.05       0
Bank Sta=4986.7,4990.7
Exp/Cntr=0.3,0.1

Chan Stop Cuts=-1