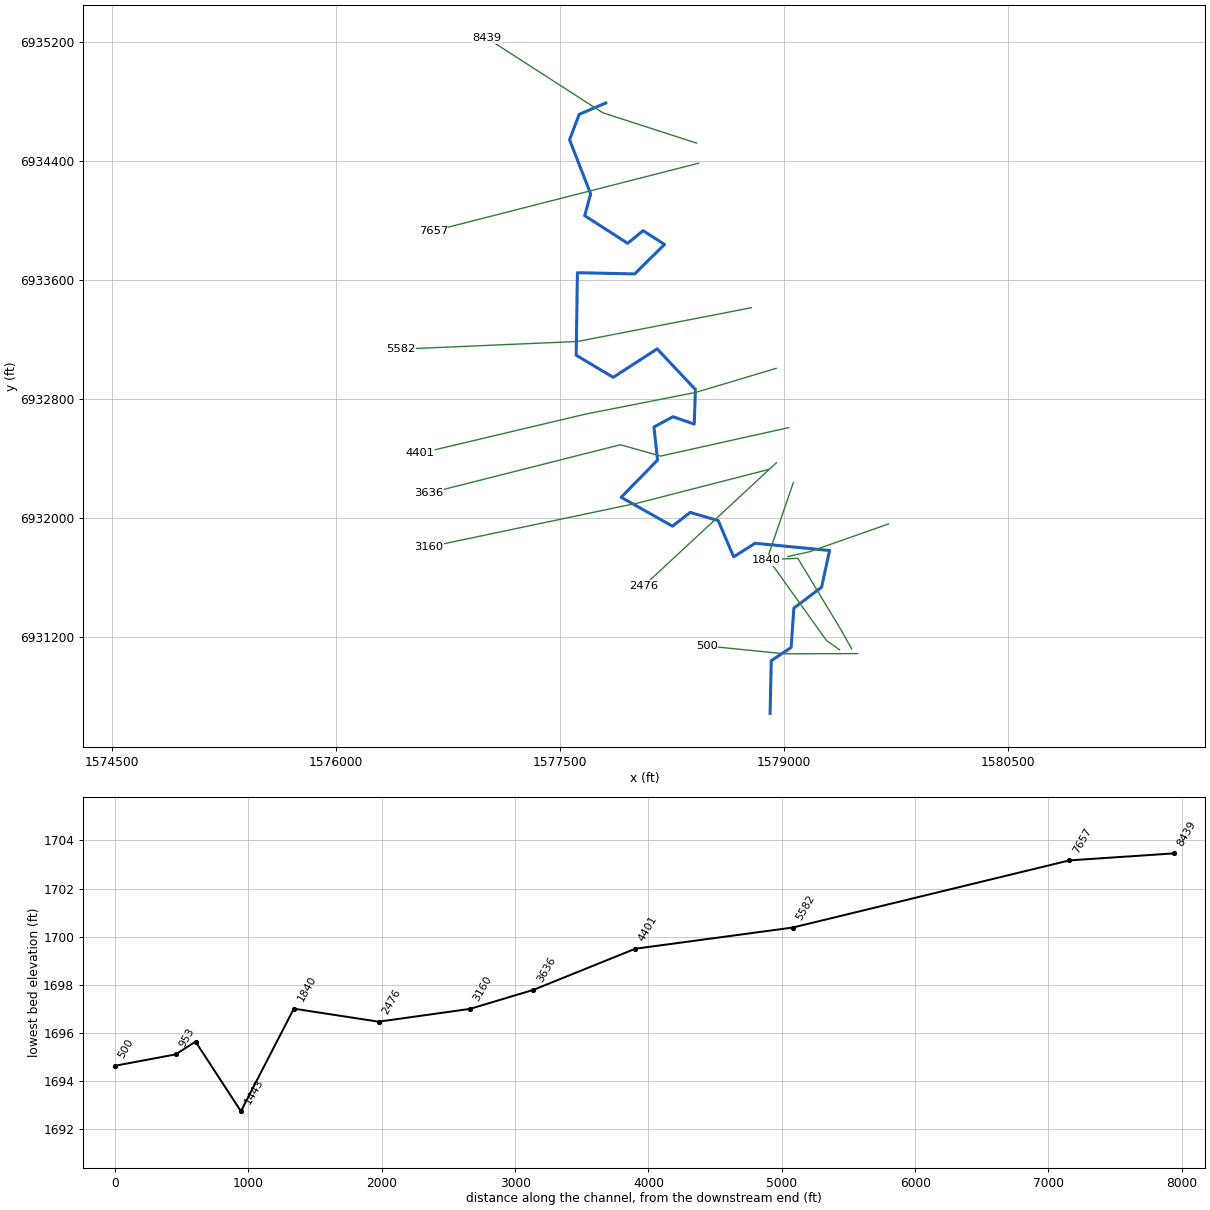
--- Deadman 26.prj (project) ---

Proj Title=Deadman 26 Base Level Engineering
Current Plan=p01
Default Exp/Contr=0.3,0.1
English Units
Geom File=g01
Flow File=f01
Plan File=p01
BEGIN DESCRIPTION:
Deadman 26
END DESCRIPTION:

--- Deadman 26.p01 (plan) ---

Plan Title=Multiple Run
Short Identifier=Multiple
Geom File=g01
Flow File=f01
Subcritical Flow
K Sum by GR= 0
Std Step Tol= 0.01
Critical Tol= 0.01
Num of Std Step Trials= 20
Max Error Tol= 0.3
Flow Tol Ratio= 0.001
Split Flow NTrial= 30
Split Flow Tol= 0.02
Split Flow Ratio= 0.02
Log Output Level= 0
Friction Slope Method= 1
Unsteady Friction Slope Method= 2
Unsteady Bridges Friction Slope Method= 1
Parabolic Critical Depth
Global Vel Dist=  1 , 1 , 1
Global Log Level= 0
CheckData=True
Encroach Param= -1, 0, 0, 0
BEGIN DESCRIPTION:
Multiple Run
END DESCRIPTION:

--- Deadman 26.f01 (steady flow) ---

Flow Title=Multiple
Number of Profiles=7
Profile Names=10-year,25-year,50-year,1pct_min,100-year,1pct_plu,500-year
River Rch & RM= Deadman 26,Reach-1,8439
     135     176     208     122     244     487     339
River Rch & RM= Deadman 26,Reach-1,4401
     163     214     253     149     297     592     415
Boundary for River Rch & Prof#=Deadman 26,Reach-1,1
Up Type=0
Dn Type=3
Dn Slope=0.007
Boundary for River Rch & Prof#=Deadman 26,Reach-1,2
Up Type=0
Dn Type=3
Dn Slope=0.007
Boundary for River Rch & Prof#=Deadman 26,Reach-1,3
Up Type=0
Dn Type=3
Dn Slope=0.007
Boundary for River Rch & Prof#=Deadman 26,Reach-1,4
Up Type=0
Dn Type=3
Dn Slope=0.007
Boundary for River Rch & Prof#=Deadman 26,Reach-1,5
Up Type=0
Dn Type=3
Dn Slope=0.007
Boundary for River Rch & Prof#=Deadman 26,Reach-1,6
Up Type=0
Dn Type=3
Dn Slope=0.007
Boundary for River Rch & Prof#=Deadman 26,Reach-1,7
Up Type=0
Dn Type=3
Dn Slope=0.007

--- Deadman 26.g01 (geometry) ---

Geom Title=Existing Conditions

River Reach=Deadman 26,Reach-1
Reach XY= 30
      1577805.00      6934788.00      1577627.31      6934711.82
      1577562.64      6934541.33      1577704.05      6934177.51
      1577664.12      6934031.24      1577951.67      6933845.62
      1578054.91      6933930.69      1578198.02      6933838.22
      1577999.11      6933640.15      1577615.32      6933648.19
      1577607.05      6933093.84      1577855.01      6932945.53
      1578149.13      6933136.50      1578405.33      6932863.21
      1578397.19      6932631.15      1578255.09      6932680.69
      1578127.55      6932611.85      1578151.63      6932389.28
      1577908.09      6932139.63      1578251.67      6931945.61
      1578370.34      6932038.04      1578557.98      6931982.48
      1578661.04      6931739.58      1578804.90      6931830.67
      1579303.46      6931782.20      1579249.54      6931535.54
      1579064.19      6931394.95      1579045.96      6931130.99
      1578912.89      6931041.58      1578905.00      6930688.00

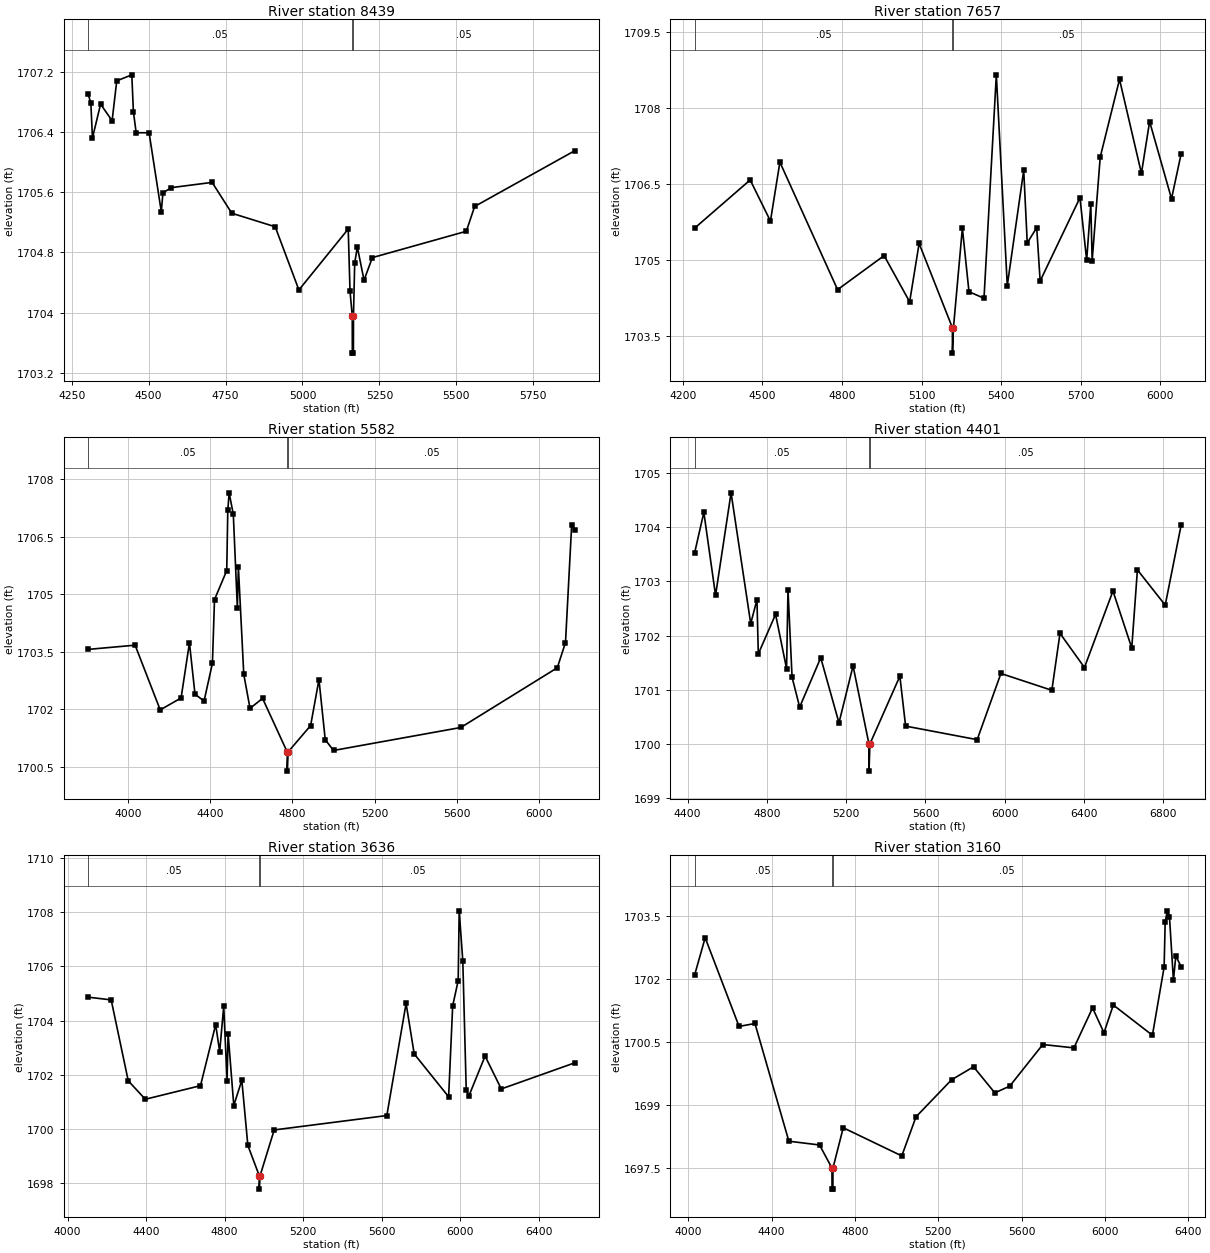
Type RM Length L Ch R = 1,8439,782,782,782
BEGIN DESCRIPTION:
Deadman 26 3.0
END DESCRIPTION:
XS GIS Cut Line= 3
      1578413.54      6934518.70      1577785.44      6934722.41
      1577011.87      6935222.61
#Sta/Elev= 30
  4303.2 1706.90  4312.0 1706.79  4317.3 1706.32  4343.7 1706.77  4381.2 1706.55
  4396.3 1707.08  4445.2 1707.16  4450.4 1706.67  4459.4 1706.39  4501.4 1706.39
  4541.1 1705.34  4546.4 1705.59  4573.1 1705.66  4706.3 1705.73  4770.2 1705.32
  4911.4 1705.14  4988.4 1704.30  5148.7 1705.11  5154.6 1704.28  5161.8 1703.96
  5162.1 1703.46  5165.6 1703.46  5165.8 1703.96  5169.8 1704.66  5178.4 1704.87
  5200.1 1704.43  5227.2 1704.73  5532.6 1705.08  5559.7 1705.41  5884.7 1706.15
#Mann=3,-1,0
  4303.2    0.05       0  5161.8   0.035       0  5165.8    0.05       0
Bank Sta=5161.8,5165.8
Exp/Cntr=0.3,0.1

Type RM Length L Ch R = 1,7657,2075,2075,2075
BEGIN DESCRIPTION:
Mapping XS 81c4d3e2
END DESCRIPTION:
XS GIS Cut Line= 2
      1578427.41      6934383.95      1576650.05      6933928.45
#Sta/Elev= 30
  4244.2 1705.63  4453.9 1706.58  4530.3 1705.77  4565.9 1706.93  4783.5 1704.42
  4959.0 1705.09  5055.3 1704.18  5091.0 1705.33  5216.5 1703.67  5216.7 1703.17
  5220.5 1703.67  5254.1 1705.63  5279.0 1704.38  5335.7 1704.25  5382.2 1708.65
  5423.5 1704.50  5485.5 1706.77  5498.8 1705.34  5534.5 1705.64  5547.4 1704.59
  5697.6 1706.23  5722.9 1705.00  5738.4 1706.11  5743.6 1704.99  5774.0 1707.03
  5846.8 1708.56  5929.4 1706.71  5960.3 1707.73  6042.9 1706.21  6079.0 1707.09
#Mann=3,-1,0
  4244.2    0.05       0  5216.5    0.05       0  5220.5    0.05       0
Bank Sta=5216.5,5220.5
Exp/Cntr=0.3,0.1

Type RM Length L Ch R = 1,5582,1181,1181,1181
BEGIN DESCRIPTION:
Deadman 26 2.0
END DESCRIPTION:
XS GIS Cut Line= 3
      1578779.96      6933412.99      1577615.68      6933186.14
      1576430.57      6933134.86
#Sta/Elev= 30
  3803.4 1703.56  4032.6 1703.67  4154.9 1701.98  4256.7 1702.29  4297.5 1703.73
  4324.6 1702.39  4368.8 1702.21  4409.6 1703.20  4419.7 1704.86  4479.4 1705.62
  4484.5 1707.19  4491.1 1707.65  4511.4 1707.09  4531.1 1704.65  4536.2 1705.71
  4562.4 1702.91  4592.9 1702.02  4654.1 1702.28  4774.3 1700.88  4774.5 1700.38
  4778.4 1700.88  4888.4 1701.57  4929.1 1702.77  4959.7 1701.20  5000.3 1700.92
  5620.8 1701.52  6091.3 1703.08  6131.3 1703.74  6161.4 1706.81  6175.8 1706.69
#Mann=3,-1,0
  3803.4    0.05       0  4774.3    0.05       0  4778.4    0.05       0
Bank Sta=4774.3,4778.4
Exp/Cntr=0.3,0.1

Type RM Length L Ch R = 1,4401,765,765,765
BEGIN DESCRIPTION:
Mapping XS 203ff9b0
END DESCRIPTION:
XS GIS Cut Line= 4
      1578946.35      6933005.97      1578409.75      6932844.76
      1577665.92      6932697.38      1576560.55      6932434.86
#Sta/Elev= 30
  4435.2 1703.52  4481.9 1704.27  4541.0 1702.74  4619.3 1704.63  4718.4 1702.22
  4749.9 1702.66  4756.7 1701.66  4843.8 1702.39  4899.3 1701.39  4906.5 1702.84
  4927.1 1701.23  4965.4 1700.68  5071.7 1701.59  5163.7 1700.39  5234.8 1701.44
  5315.0 1700.00  5315.4 1699.50  5319.7 1700.00  5471.0 1701.25  5499.9 1700.33
  5861.0 1700.08  5980.8 1701.30  6237.8 1700.99  6278.9 1702.04  6402.3 1701.41
  6546.1 1702.82  6641.0 1701.77  6669.5 1703.21  6809.8 1702.56  6889.9 1704.03
#Mann=3,-1,0
  4435.2    0.05       0  5315.0    0.05       0  5319.7    0.05       0
Bank Sta=5315,5319.7
Exp/Cntr=0.3,0.1

Type RM Length L Ch R = 1,3636,476,476,476
BEGIN DESCRIPTION:
Mapping XS a04f3c8a
END DESCRIPTION:
XS GIS Cut Line= 4
      1579029.26      6932607.58      1578172.55      6932416.43
      1577903.12      6932492.43      1576622.77      6932167.73
#Sta/Elev= 30
  4104.6 1704.86  4222.1 1704.76  4309.0 1701.78  4395.9 1701.10  4677.1 1701.60
  4754.5 1703.85  4774.9 1702.85  4795.4 1704.52  4812.6 1701.79  4817.7 1703.52
  4846.7 1700.87  4887.7 1701.80  4918.4 1699.40  4976.2 1698.29  4976.5 1697.79
  4980.9 1698.29  5052.6 1699.97  5626.4 1700.50  5724.6 1704.63  5765.9 1702.77
  5941.3 1701.19  5961.9 1704.54  5990.0 1705.47  5995.1 1708.04  6013.5 1706.20
  6030.9 1701.45  6044.4 1701.22  6127.0 1702.69  6209.5 1701.48  6583.2 1702.44
#Mann=3,-1,0
  4104.6    0.05       0  4976.2    0.05       0  4980.9    0.05       0
Bank Sta=4976.2,4980.9
Exp/Cntr=0.3,0.1

Type RM Length L Ch R = 1,3160,684,684,684
BEGIN DESCRIPTION:
Mapping XS 99f3c016
END DESCRIPTION:
XS GIS Cut Line= 3
      1578895.66      6932326.62      1578029.78      6932103.24
      1576620.38      6931806.16
#Sta/Elev= 30
  4030.3 1702.09  4081.1 1702.98  4243.8 1700.87  4320.0 1700.94  4482.7 1698.14
  4630.0 1698.05  4689.5 1697.50  4689.9 1697.00  4694.0 1697.00  4694.3 1697.50
  4743.6 1698.46  5024.6 1697.79  5092.9 1698.72  5263.3 1699.60  5368.9 1699.91
  5471.1 1699.29  5542.6 1699.45  5701.2 1700.44  5850.6 1700.36  5940.0 1701.31
  5994.9 1700.72  6039.5 1701.38  6227.3 1700.66  6283.4 1702.28  6288.6 1703.36
  6298.9 1703.62  6309.1 1703.48  6328.1 1701.97  6339.7 1702.55  6364.9 1702.29
#Mann=3,-1,0
  4030.3    0.05       0  4689.5    0.05       0  4694.3    0.05       0
Bank Sta=4689.5,4694.3
Exp/Cntr=0.3,0.1

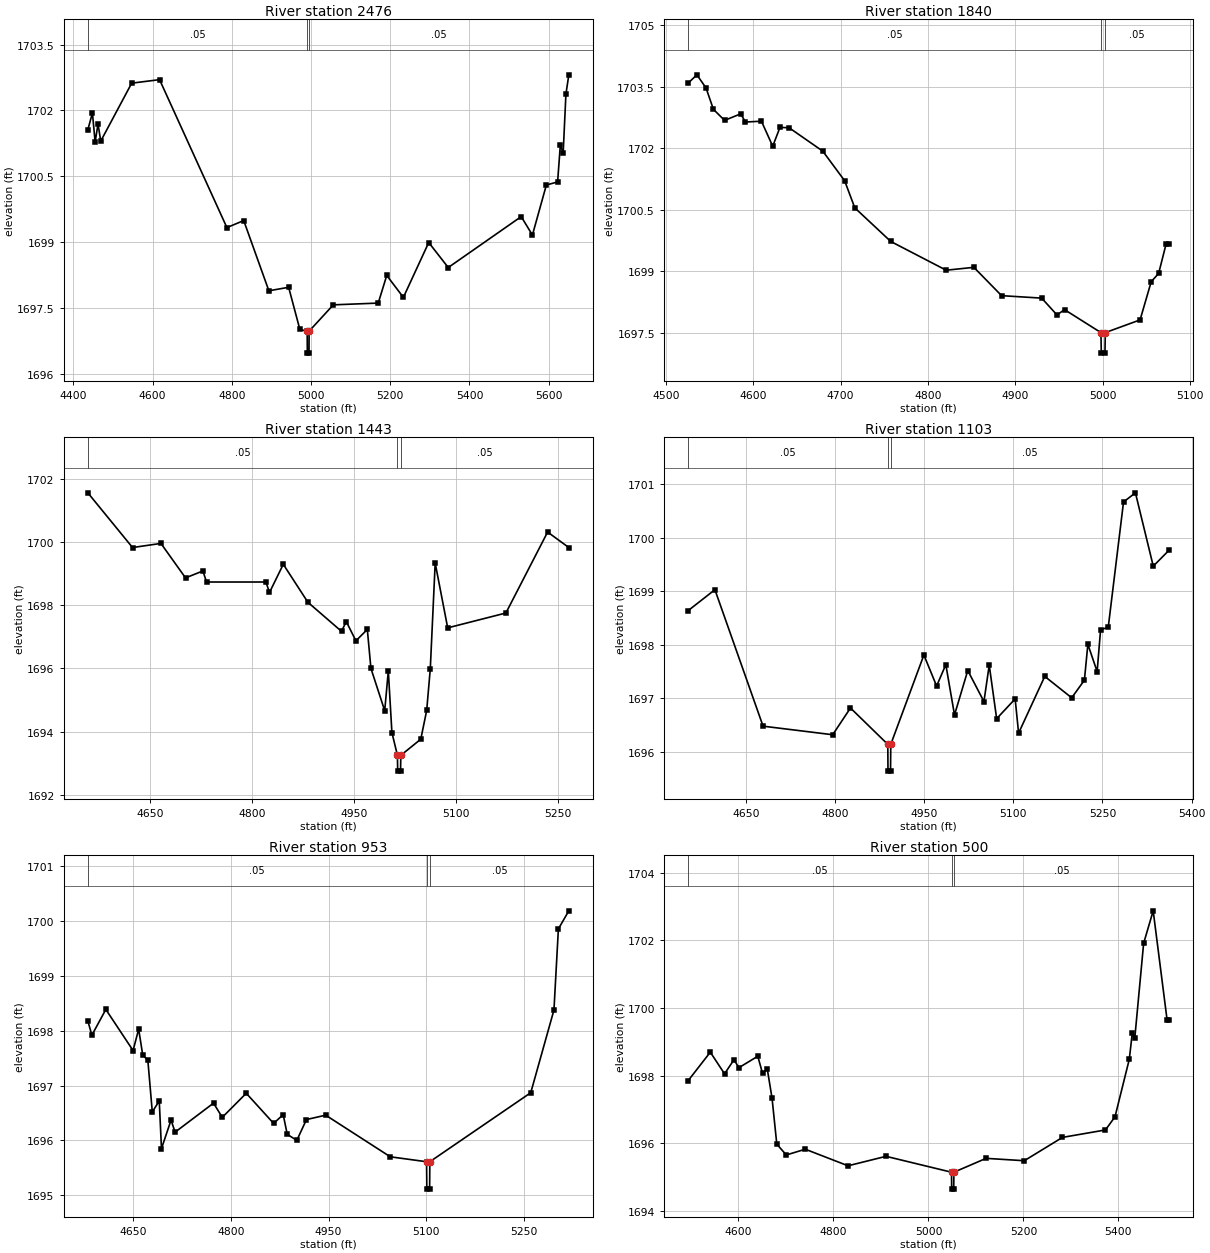
Type RM Length L Ch R = 1,2476,636,636,636
BEGIN DESCRIPTION:
Mapping XS f5dde87d
END DESCRIPTION:
XS GIS Cut Line= 2
      1578947.39      6932371.86      1578058.88      6931544.03
#Sta/Elev= 30
  4436.4 1701.56  4448.0 1701.94  4454.8 1701.28  4462.1 1701.69  4469.0 1701.30
  4547.1 1702.62  4617.5 1702.70  4787.5 1699.33  4830.0 1699.49  4893.5 1697.89
  4943.4 1697.97  4971.7 1697.01  4990.2 1696.97  4990.6 1696.47  4994.8 1696.47
  4995.1 1696.97  5056.2 1697.57  5169.6 1697.61  5191.1 1698.24  5233.1 1697.74
  5297.1 1698.99  5346.4 1698.42  5530.6 1699.58  5558.9 1699.16  5594.1 1700.30
  5622.5 1700.37  5629.3 1701.20  5636.6 1701.04  5643.5 1702.37  5650.8 1702.81
#Mann=3,-1,0
  4436.4    0.05       0  4990.2   0.035       0  4995.1    0.05       0
Bank Sta=4990.2,4995.1
Exp/Cntr=0.3,0.1

Type RM Length L Ch R = 1,1840,397,397,397
BEGIN DESCRIPTION:
Mapping XS 5aa208d1
END DESCRIPTION:
XS GIS Cut Line= 2
      1579060.27      6932237.34      1578882.32      6931716.50
#Sta/Elev= 30
  4525.7 1703.59  4535.6 1703.79  4546.1 1703.47  4554.5 1702.95  4567.3 1702.68
  4585.8 1702.84  4591.1 1702.64  4609.5 1702.66  4622.4 1702.05  4630.7 1702.51
  4641.2 1702.50  4679.7 1701.93  4704.7 1701.21  4716.3 1700.55  4757.5 1699.73
  4820.9 1699.03  4852.6 1699.10  4884.3 1698.41  4930.2 1698.35  4947.7 1697.94
  4956.3 1698.07  4998.0 1697.51  4998.4 1697.01  5002.6 1697.01  5003.0 1697.51
  5042.8 1697.82  5055.5 1698.75  5064.0 1698.95  5072.7 1699.68  5076.1 1699.68
#Mann=3,-1,0
  4525.7    0.05       0  4998.0   0.035       0  5003.0    0.05       0
Bank Sta=4998,5003
Exp/Cntr=0.3,0.1

Type RM Length L Ch R = 1,1443,340,340,340
BEGIN DESCRIPTION:
Mapping XS baa55c39
END DESCRIPTION:
XS GIS Cut Line= 3
      1579697.02      6931960.45      1579169.70      6931773.93
      1579024.57      6931741.68
#Sta/Elev= 30
  4558.3 1701.55  4624.1 1699.82  4665.9 1699.95  4702.1 1698.86  4727.7 1699.08
  4733.0 1698.73  4820.4 1698.73  4825.7 1698.40  4846.0 1699.29  4882.2 1698.09
  4931.7 1697.17  4938.7 1697.48  4952.9 1696.87  4969.7 1697.23  4975.0 1696.00
  4995.3 1694.66  5000.6 1695.92  5005.9 1693.97  5014.0 1693.25  5014.4 1692.75
  5018.6 1692.75  5019.0 1693.25  5048.4 1693.76  5057.1 1694.67  5062.4 1695.99
  5069.6 1699.33  5088.0 1697.28  5173.7 1697.75  5235.1 1700.31  5266.3 1699.82
#Mann=3,-1,0
  4558.3    0.05       0  5014.0    0.05       0  5019.0    0.05       0
Bank Sta=5014,5019
Exp/Cntr=0.3,0.1

Type RM Length L Ch R = 1,1103,150,150,150
BEGIN DESCRIPTION:
Mapping XS d85630ef
END DESCRIPTION:
XS GIS Cut Line= 4
      1579450.92      6931121.86      1579372.78      6931260.78
      1579090.66      6931729.53      1578988.23      6931725.27
#Sta/Elev= 30
  4553.2 1698.64  4598.1 1699.03  4679.1 1696.48  4796.2 1696.32  4826.1 1696.82
  4888.9 1696.14  4889.2 1695.64  4893.5 1695.64  4893.9 1696.14  4949.6 1697.81
  4971.0 1697.23  4986.5 1697.63  5001.1 1696.69  5023.4 1697.52  5050.6 1696.94
  5059.5 1697.62  5072.0 1696.62  5103.1 1696.99  5108.9 1696.35  5152.9 1697.41
  5198.2 1697.01  5219.6 1697.34  5225.4 1698.01  5241.0 1697.50  5246.8 1698.28
  5259.7 1698.33  5285.4 1700.67  5305.4 1700.84  5335.4 1699.47  5362.2 1699.77
#Mann=3,-1,0
  4553.2    0.05       0  4888.9    0.05       0  4893.9    0.05       0
Bank Sta=4888.9,4893.9
Exp/Cntr=0.3,0.1

Type RM Length L Ch R = 1,953,453,453,453
BEGIN DESCRIPTION:
Mapping XS 6385dd0f
END DESCRIPTION:
XS GIS Cut Line= 3
      1579370.08      6931115.28      1579282.54      6931177.49
      1578916.38      6931691.03
#Sta/Elev= 30
  4580.6 1698.18  4586.8 1697.92  4608.2 1698.39  4650.0 1697.64  4658.6 1698.03
  4664.8 1697.56  4672.7 1697.46  4679.5 1696.52  4690.2 1696.72  4693.6 1695.85
  4708.3 1696.37  4714.5 1696.15  4773.5 1696.68  4786.9 1696.42  4823.7 1696.86
  4865.7 1696.31  4880.4 1696.47  4886.6 1696.11  4901.3 1696.00  4916.1 1696.38
  4945.6 1696.46  5044.8 1695.70  5100.4 1695.61  5100.8 1695.11  5105.1 1695.11
  5105.4 1695.61  5260.3 1696.87  5295.9 1698.38  5302.7 1699.86  5318.7 1700.19
#Mann=3,-1,0
  4580.6    0.05       0  5100.4   0.035       0  5105.4    0.05       0
Bank Sta=5100.4,5105.4
Exp/Cntr=0.3,0.1

Type RM Length L Ch R = 1,500,0,0,0
BEGIN DESCRIPTION:
Deadman 26 1.0
END DESCRIPTION:
XS GIS Cut Line= 3
      1579491.50      6931089.69      1579005.00      6931088.00
      1578481.44      6931140.62
#Sta/Elev= 30
  4494.2 1697.85  4540.7 1698.69  4570.7 1698.05  4590.7 1698.47  4600.7 1698.23
  4640.7 1698.57  4650.7 1698.06  4660.7 1698.19  4670.7 1697.33  4680.7 1695.97
  4700.7 1695.65  4740.7 1695.82  4830.7 1695.33  4910.7 1695.61  5048.6 1695.14
  5048.9 1694.64  5053.2 1694.64  5053.6 1695.14  5121.4 1695.55  5201.8 1695.48
  5282.2 1696.17  5372.7 1696.39  5392.8 1696.78  5422.9 1698.48  5429.3 1699.27
  5434.4 1699.10  5453.1 1701.91  5473.2 1702.87  5502.6 1699.63  5506.9 1699.63
#Mann=3,-1,0
  4494.2    0.05       0  5048.6   0.035       0  5053.6    0.05       0
Bank Sta=5048.6,5053.6
Exp/Cntr=0.3,0.1

Chan Stop Cuts=-1