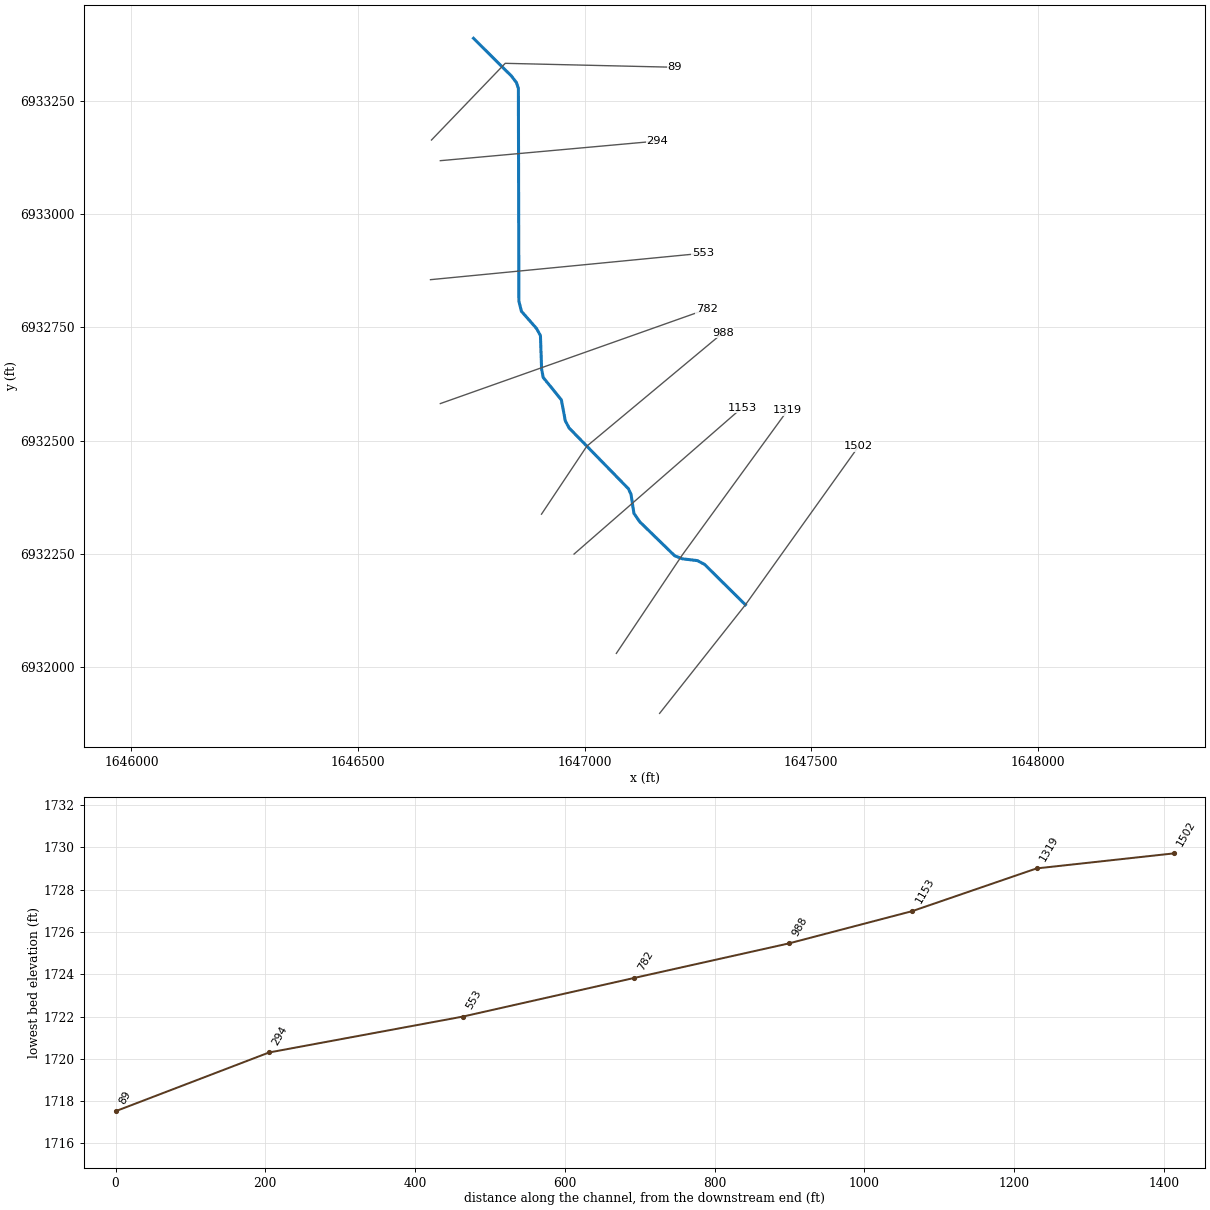
--- Deadman 27.prj (project) ---

Proj Title=Deadman 27 Base Level Engineering
Current Plan=p01
Default Exp/Contr=0.3,0.1
English Units
Geom File=g01
Flow File=f01
Plan File=p01
BEGIN DESCRIPTION:
Deadman 27
END DESCRIPTION:

--- Deadman 27.p01 (plan) ---

Plan Title=Multiple Run
Short Identifier=Multiple
Geom File=g01
Flow File=f01
Subcritical Flow
K Sum by GR= 0
Std Step Tol= 0.01
Critical Tol= 0.01
Num of Std Step Trials= 20
Max Error Tol= 0.3
Flow Tol Ratio= 0.001
Split Flow NTrial= 30
Split Flow Tol= 0.02
Split Flow Ratio= 0.02
Log Output Level= 0
Friction Slope Method= 1
Unsteady Friction Slope Method= 2
Unsteady Bridges Friction Slope Method= 1
Parabolic Critical Depth
Global Vel Dist=  1 , 1 , 1
Global Log Level= 0
CheckData=True
Encroach Param= -1, 0, 0, 0
BEGIN DESCRIPTION:
Multiple Run
END DESCRIPTION:

--- Deadman 27.f01 (steady flow) ---

Flow Title=Multiple
Number of Profiles=7
Profile Names=10-year,25-year,50-year,1pct_min,100-year,1pct_plu,500-year
River Rch & RM= Deadman 27,Reach-1,1502
     232     320     392     240     479     955     721
River Rch & RM= Deadman 27,Reach-1,1319
     235     324     397     243     484     966     729
Boundary for River Rch & Prof#=Deadman 27,Reach-1,1
Up Type=0
Dn Type=3
Dn Slope=0.005
Boundary for River Rch & Prof#=Deadman 27,Reach-1,2
Up Type=0
Dn Type=3
Dn Slope=0.005
Boundary for River Rch & Prof#=Deadman 27,Reach-1,3
Up Type=0
Dn Type=3
Dn Slope=0.005
Boundary for River Rch & Prof#=Deadman 27,Reach-1,4
Up Type=0
Dn Type=3
Dn Slope=0.005
Boundary for River Rch & Prof#=Deadman 27,Reach-1,5
Up Type=0
Dn Type=3
Dn Slope=0.005
Boundary for River Rch & Prof#=Deadman 27,Reach-1,6
Up Type=0
Dn Type=3
Dn Slope=0.005
Boundary for River Rch & Prof#=Deadman 27,Reach-1,7
Up Type=0
Dn Type=3
Dn Slope=0.005

--- Deadman 27.g01 (geometry) ---

Geom Title=Existing Conditions

River Reach=Deadman 27,Reach-1
Reach XY= 22
      1647355.00      6932138.00      1647264.70      6932227.28
      1647248.95      6932235.48      1647215.63      6932239.53
      1647198.93      6932246.14      1647121.64      6932321.29
      1647108.97      6932339.64      1647102.46      6932381.95
      1647096.84      6932394.05      1646965.76      6932528.32
      1646957.50      6932544.03      1646948.86      6932590.17
      1646908.82      6932639.58      1646905.23      6932658.09
      1646902.64      6932732.02      1646894.11      6932747.63
      1646860.74      6932785.66      1646855.07      6932808.03
      1646853.98      6933277.58      1646849.60      6933290.48
      1646838.67      6933304.81      1646755.00      6933388.00

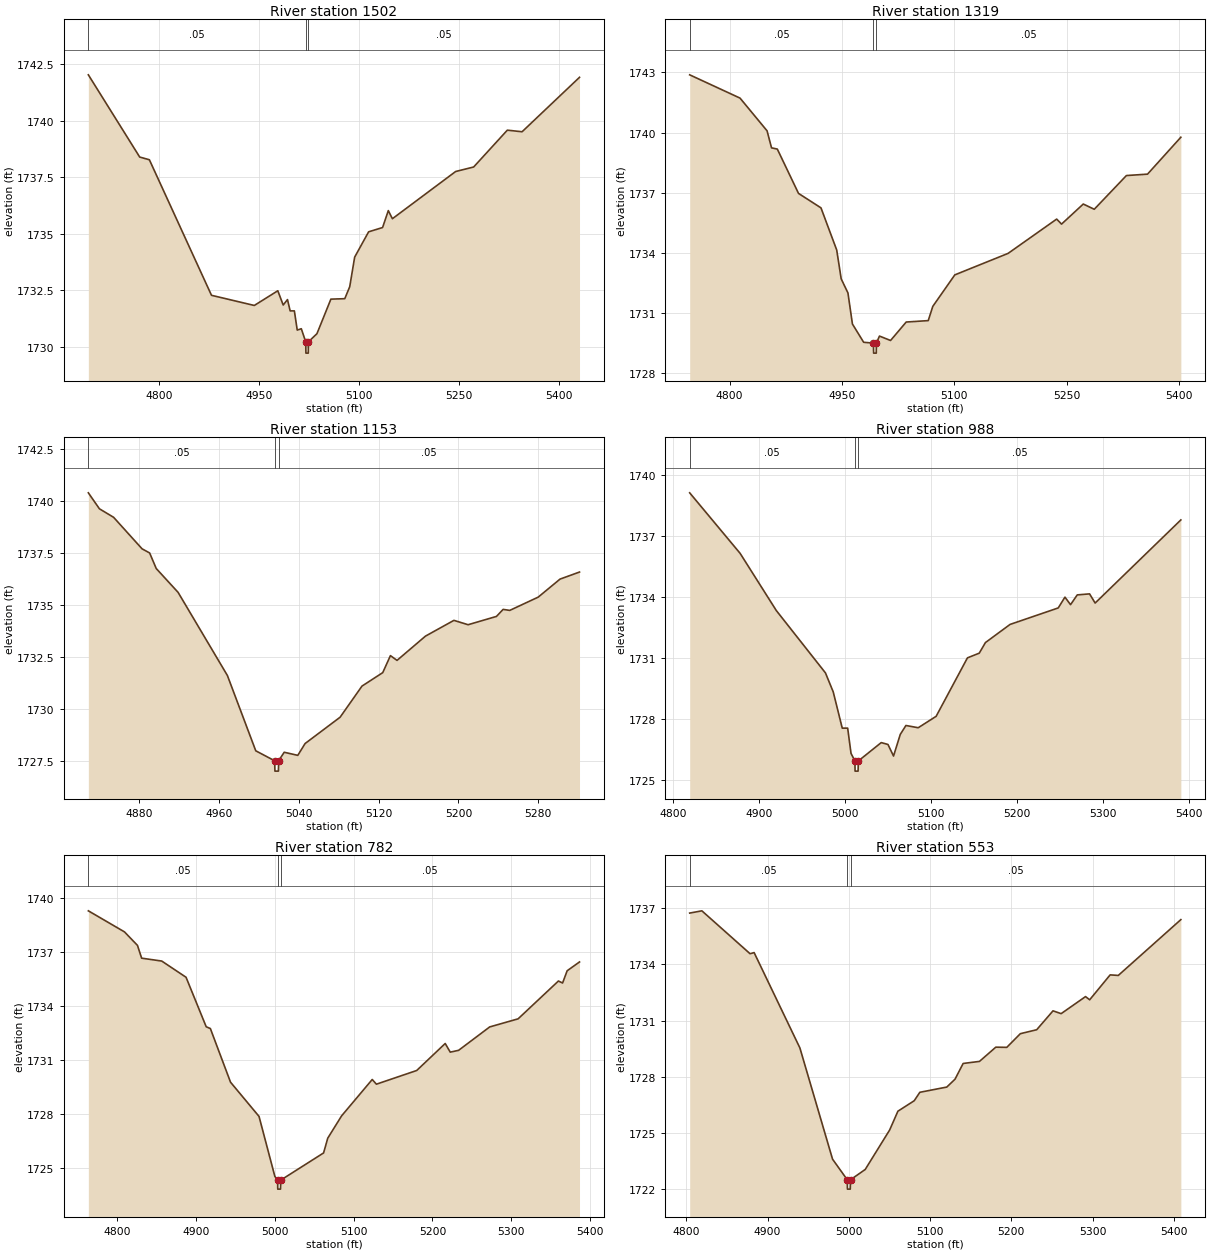
Type RM Length L Ch R = 1,1502,183,183,183
BEGIN DESCRIPTION:
Deadman 27 3.0
END DESCRIPTION:
XS GIS Cut Line= 3
      1647165.64      6931898.39      1647355.00      6932138.00
      1647604.99      6932487.99
#Sta/Elev= 30
  4694.6 1742.04  4771.5 1738.40  4786.0 1738.28  4879.0 1732.28  4943.1 1731.83
  4978.3 1732.48  4986.4 1731.85  4992.8 1732.09  4996.8 1731.59  5003.1 1731.59
  5007.4 1730.74  5013.5 1730.80  5020.1 1730.22  5020.4 1729.72  5023.9 1729.72
  5024.1 1730.22  5036.9 1730.58  5057.8 1732.11  5078.6 1732.13  5086.0 1732.66
  5093.4 1733.97  5114.3 1735.09  5135.2 1735.28  5143.8 1736.03  5149.9 1735.67
  5244.6 1737.76  5271.6 1737.96  5322.0 1739.59  5344.1 1739.52  5430.1 1741.93
#Mann=3,-1,0
  4694.6    0.05       0  5020.1    0.03       0  5024.1    0.05       0
Bank Sta=5020.1,5024.1
Exp/Cntr=0.3,0.1

Type RM Length L Ch R = 1,1319,166,166,166
BEGIN DESCRIPTION:
Mapping XS 48fc3472
END DESCRIPTION:
XS GIS Cut Line= 3
      1647070.15      6932030.77      1647215.56      6932247.79
      1647447.76      6932566.80
#Sta/Elev= 30
  4746.6 1742.88  4813.8 1741.72  4849.9 1740.09  4855.9 1739.24  4863.6 1739.18
  4891.9 1736.97  4921.9 1736.25  4942.9 1734.15  4948.9 1732.71  4957.9 1732.01
  4963.9 1730.46  4978.9 1729.55  4991.9 1729.51  4992.2 1729.01  4995.7 1729.01
  4995.9 1729.51  5000.0 1729.86  5014.8 1729.64  5035.7 1730.56  5065.1 1730.63
  5071.2 1731.34  5100.6 1732.91  5171.7 1733.98  5236.6 1735.69  5243.1 1735.44
  5272.1 1736.44  5286.8 1736.18  5329.7 1737.86  5357.9 1737.93  5402.4 1739.77
#Mann=3,-1,0
  4746.6    0.05       0  4991.9    0.03       0  4995.9    0.05       0
Bank Sta=4991.9,4995.9
Exp/Cntr=0.3,0.1

Type RM Length L Ch R = 1,1153,165,165,165
BEGIN DESCRIPTION:
Mapping XS 5aba6e61
END DESCRIPTION:
XS GIS Cut Line= 2
      1646976.82      6932249.94      1647347.76      6932573.16
#Sta/Elev= 30
  4829.3 1740.41  4840.4 1739.64  4854.6 1739.23  4883.1 1737.71  4890.7 1737.51
  4897.3 1736.76  4919.2 1735.61  4968.6 1731.60  4997.0 1727.97  5015.9 1727.49
  5016.2 1726.99  5019.7 1726.99  5019.9 1727.49  5025.5 1727.90  5039.1 1727.75
  5046.4 1728.32  5081.5 1729.59  5103.4 1731.09  5124.2 1731.74  5131.9 1732.56
  5138.5 1732.33  5167.0 1733.50  5195.5 1734.26  5209.7 1734.05  5238.1 1734.45
  5244.8 1734.79  5251.4 1734.74  5279.9 1735.38  5301.8 1736.25  5321.3 1736.59
#Mann=3,-1,0
  4829.3    0.05       0  5015.9    0.03       0  5019.9    0.05       0
Bank Sta=5015.9,5019.9
Exp/Cntr=0.3,0.1

Type RM Length L Ch R = 1,988,206,206,206
BEGIN DESCRIPTION:
Deadman 27 2.0
END DESCRIPTION:
XS GIS Cut Line= 3
      1646904.98      6932337.97      1647005.00      6932488.00
      1647304.98      6932737.98
#Sta/Elev= 30
  4819.6 1739.12  4878.2 1736.15  4920.3 1733.34  4977.4 1730.28  4986.4 1729.35
  4996.9 1727.57  5003.2 1727.57  5007.1 1726.33  5011.6 1725.96  5011.8 1725.46
  5015.3 1725.46  5015.6 1725.96  5042.2 1726.86  5050.0 1726.77  5056.5 1726.20
  5064.3 1727.26  5070.9 1727.70  5085.2 1727.59  5106.0 1728.15  5142.4 1731.02
  5156.1 1731.25  5163.3 1731.77  5191.9 1732.66  5247.9 1733.47  5255.7 1734.00
  5262.2 1733.63  5270.0 1734.11  5284.3 1734.16  5290.8 1733.71  5390.4 1737.79
#Mann=3,-1,0
  4819.6    0.05       0  5011.6    0.03       0  5015.6    0.05       0
Bank Sta=5011.6,5015.6
Exp/Cntr=0.3,0.1

Type RM Length L Ch R = 1,782,229,229,229
BEGIN DESCRIPTION:
Mapping XS 2def8a0b
END DESCRIPTION:
XS GIS Cut Line= 2
      1646681.72      6932582.00      1647269.82      6932790.33
#Sta/Elev= 30
  4763.0 1739.29  4808.9 1738.12  4825.4 1737.37  4830.7 1736.66  4856.2 1736.50
  4887.1 1735.60  4912.7 1732.85  4918.0 1732.75  4943.6 1729.77  4979.8 1727.87
  4999.9 1724.54  5003.4 1724.33  5003.6 1723.83  5007.1 1723.83  5007.4 1724.33
  5061.8 1725.84  5067.1 1726.66  5084.7 1727.90  5123.6 1729.92  5128.9 1729.66
  5180.1 1730.42  5216.3 1731.92  5222.7 1731.44  5233.3 1731.54  5272.8 1732.84
  5308.9 1733.29  5360.1 1735.39  5365.4 1735.28  5371.2 1735.96  5386.9 1736.45
#Mann=3,-1,0
  4763.0    0.05       0  5003.4    0.05       0  5007.4    0.05       0
Bank Sta=5003.4,5007.4
Exp/Cntr=0.3,0.1

Type RM Length L Ch R = 1,553,259,259,259
BEGIN DESCRIPTION:
Mapping XS 8d997722
END DESCRIPTION:
XS GIS Cut Line= 2
      1646660.03      6932855.44      1647261.60      6932913.86
#Sta/Elev= 30
  4804.2 1736.74  4819.2 1736.86  4878.5 1734.57  4883.5 1734.63  4939.8 1729.54
  4980.0 1723.60  4998.1 1722.50  4998.3 1722.00  5001.8 1722.00  5002.1 1722.50
  5020.2 1723.05  5050.3 1725.16  5060.4 1726.16  5080.5 1726.72  5087.4 1727.17
  5120.6 1727.45  5130.7 1727.87  5140.7 1728.71  5160.8 1728.82  5180.9 1729.58
  5194.4 1729.57  5211.1 1730.30  5231.2 1730.51  5251.3 1731.52  5261.3 1731.37
  5291.3 1732.28  5296.4 1732.11  5321.6 1733.44  5331.6 1733.41  5408.6 1736.39
#Mann=3,-1,0
  4804.2    0.05       0  4998.1    0.03       0  5002.1    0.05       0
Bank Sta=4998.1,5002.1
Exp/Cntr=0.3,0.1

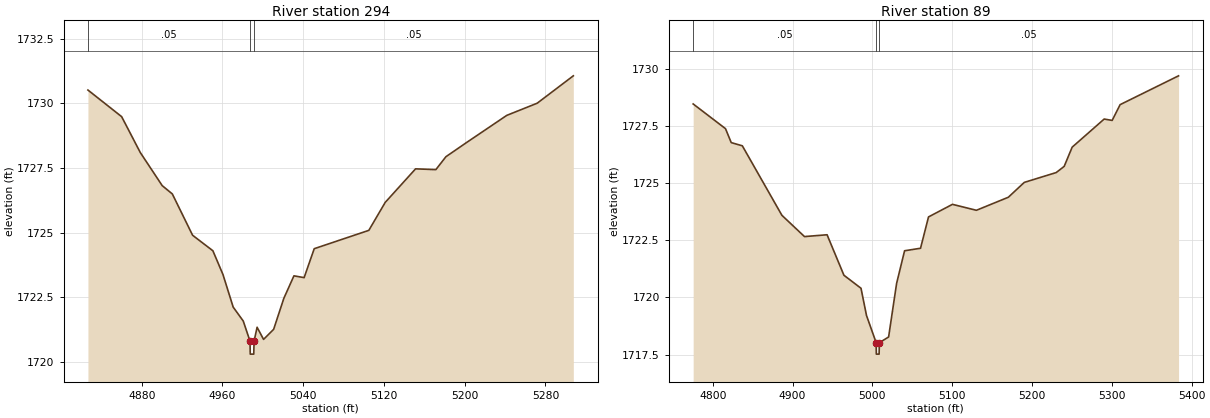
Type RM Length L Ch R = 1,294,205,205,205
BEGIN DESCRIPTION:
Mapping XS c5971901
END DESCRIPTION:
XS GIS Cut Line= 2
      1646681.72      6933118.02      1647160.66      6933161.36
#Sta/Elev= 30
  4826.7 1730.52  4860.1 1729.49  4878.6 1728.10  4900.3 1726.82  4910.3 1726.50
  4930.4 1724.90  4950.5 1724.30  4960.5 1723.38  4970.6 1722.12  4980.6 1721.58
  4987.3 1720.80  4987.5 1720.30  4991.0 1720.30  4991.3 1720.80  4994.3 1721.34
  5000.7 1720.87  5010.7 1721.26  5020.8 1722.46  5030.8 1723.33  5040.9 1723.26
  5050.9 1724.38  5105.0 1725.09  5121.2 1726.17  5151.3 1727.47  5171.4 1727.44
  5181.4 1727.94  5201.5 1728.48  5241.7 1729.54  5271.8 1730.01  5307.6 1731.07
#Mann=3,-1,0
  4826.7    0.05       0  4987.3    0.03       0  4991.3    0.05       0
Bank Sta=4987.3,4991.3
Exp/Cntr=0.3,0.1

Type RM Length L Ch R = 1,89,0,0,0
BEGIN DESCRIPTION:
Deadman 27 1.0
END DESCRIPTION:
XS GIS Cut Line= 3
      1646662.19      6933163.60      1646824.93      6933332.86
      1647198.22      6933324.18
#Sta/Elev= 30
  4775.4 1728.46  4815.9 1727.38  4823.1 1726.77  4837.0 1726.63  4886.6 1723.59
  4914.9 1722.66  4943.2 1722.74  4964.3 1720.97  4985.7 1720.40  4992.6 1719.21
  5004.7 1718.02  5004.9 1717.52  5008.4 1717.52  5008.7 1718.02  5020.3 1718.27
  5030.3 1720.61  5040.3 1722.04  5060.3 1722.15  5070.3 1723.52  5100.3 1724.07
  5130.3 1723.81  5170.3 1724.38  5190.3 1725.03  5230.3 1725.46  5240.3 1725.73
  5250.3 1726.57  5290.4 1727.80  5300.4 1727.74  5310.4 1728.43  5383.6 1729.69
#Mann=3,-1,0
  4775.4    0.05       0  5004.7    0.05       0  5008.7    0.05       0
Bank Sta=5004.7,5008.7
Exp/Cntr=0.3,0.1

Chan Stop Cuts=-1