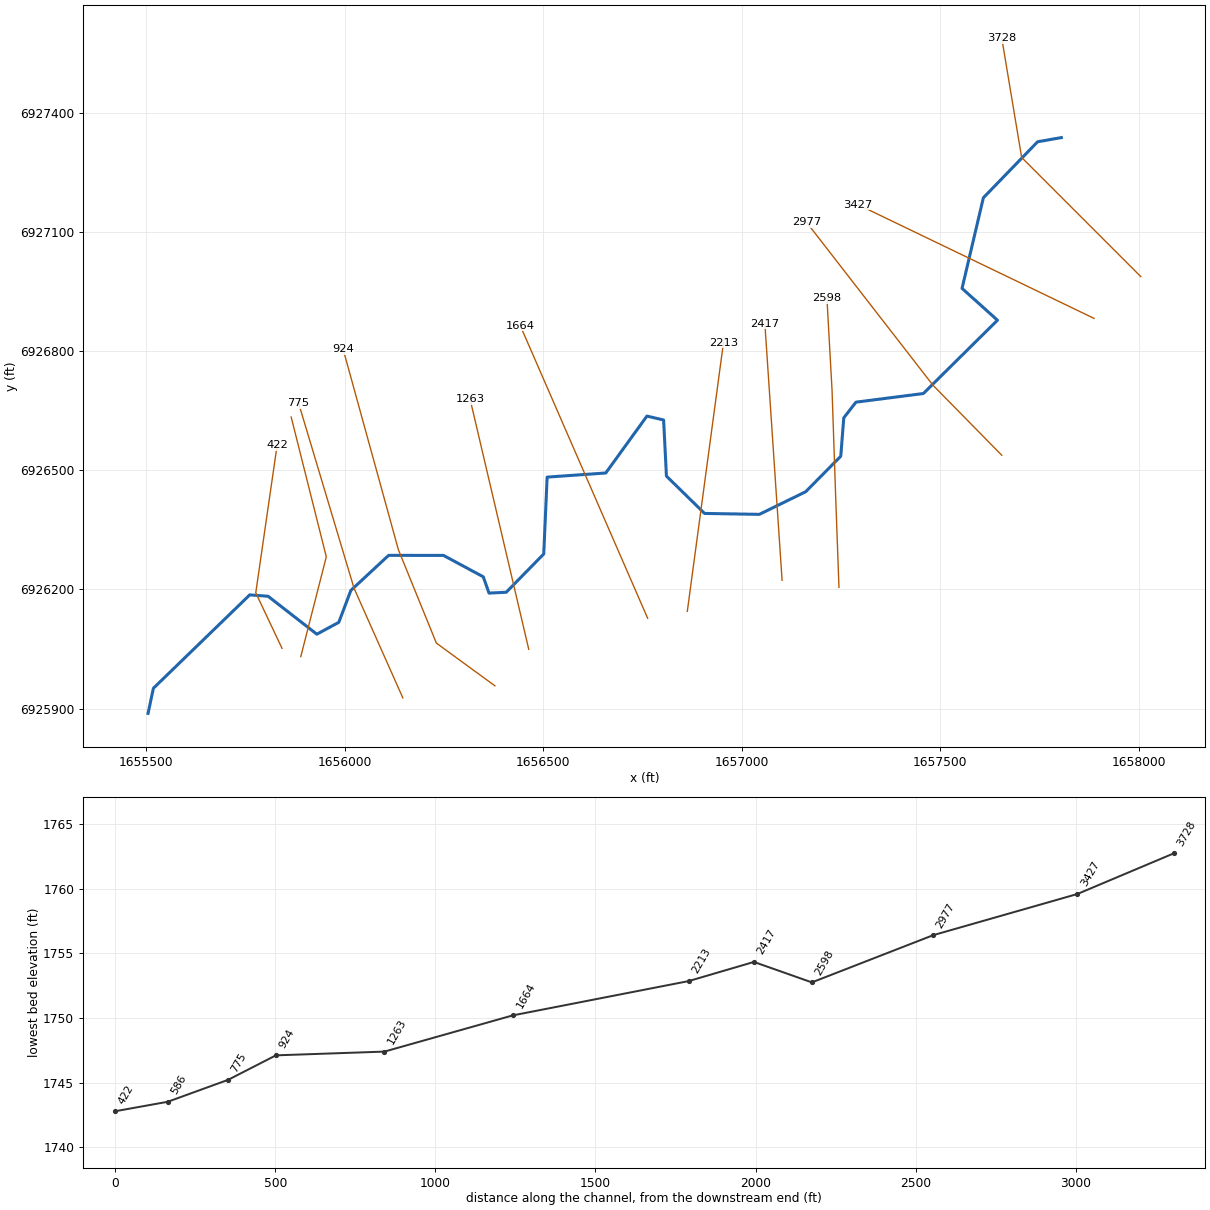
--- Deadman 28.prj (project) ---

Proj Title=Deadman 28 Base Level Engineering
Current Plan=p01
Default Exp/Contr=0.3,0.1
English Units
Geom File=g01
Flow File=f01
Plan File=p01
BEGIN DESCRIPTION:
Deadman 28
END DESCRIPTION:

--- Deadman 28.p01 (plan) ---

Plan Title=Multiple Run
Short Identifier=Multiple
Geom File=g01
Flow File=f01
Subcritical Flow
K Sum by GR= 0
Std Step Tol= 0.01
Critical Tol= 0.01
Num of Std Step Trials= 20
Max Error Tol= 0.3
Flow Tol Ratio= 0.001
Split Flow NTrial= 30
Split Flow Tol= 0.02
Split Flow Ratio= 0.02
Log Output Level= 0
Friction Slope Method= 1
Unsteady Friction Slope Method= 2
Unsteady Bridges Friction Slope Method= 1
Parabolic Critical Depth
Global Vel Dist=  1 , 1 , 1
Global Log Level= 0
CheckData=True
Encroach Param= -1, 0, 0, 0
BEGIN DESCRIPTION:
Multiple Run
END DESCRIPTION:

--- Deadman 28.f01 (steady flow) ---

Flow Title=Multiple
Number of Profiles=7
Profile Names=10-year,25-year,50-year,1pct_min,100-year,1pct_plu,500-year
River Rch & RM= Deadman 28,Reach-1,3728
     278     389     482     298     594    1184     911
Boundary for River Rch & Prof#=Deadman 28,Reach-1,1
Up Type=0
Dn Type=3
Dn Slope=0.005
Boundary for River Rch & Prof#=Deadman 28,Reach-1,2
Up Type=0
Dn Type=3
Dn Slope=0.005
Boundary for River Rch & Prof#=Deadman 28,Reach-1,3
Up Type=0
Dn Type=3
Dn Slope=0.005
Boundary for River Rch & Prof#=Deadman 28,Reach-1,4
Up Type=0
Dn Type=3
Dn Slope=0.005
Boundary for River Rch & Prof#=Deadman 28,Reach-1,5
Up Type=0
Dn Type=3
Dn Slope=0.005
Boundary for River Rch & Prof#=Deadman 28,Reach-1,6
Up Type=0
Dn Type=3
Dn Slope=0.005
Boundary for River Rch & Prof#=Deadman 28,Reach-1,7
Up Type=0
Dn Type=3
Dn Slope=0.005

--- Deadman 28.g01 (geometry) ---

Geom Title=Existing Conditions

River Reach=Deadman 28,Reach-1
Reach XY= 30
      1657805.00      6927338.00      1657745.21      6927327.49
      1657608.61      6927186.50      1657554.90      6926958.26
      1657644.09      6926878.12      1657457.45      6926693.47
      1657287.78      6926671.76      1657257.07      6926632.31
      1657249.48      6926535.56      1657161.08      6926446.13
      1657044.50      6926389.19      1656906.46      6926391.52
      1656810.46      6926485.54      1656803.34      6926626.86
      1656761.35      6926636.69      1656657.69      6926493.37
      1656510.00      6926482.99      1656501.47      6926289.45
      1656407.00      6926192.98      1656363.64      6926190.92
      1656349.24      6926231.89      1656249.09      6926285.78
      1656110.85      6926285.96      1656015.78      6926197.68
      1655985.37      6926117.31      1655930.09      6926087.38
      1655807.28      6926182.92      1655761.05      6926186.42
      1655518.47      6925951.27      1655505.00      6925888.00

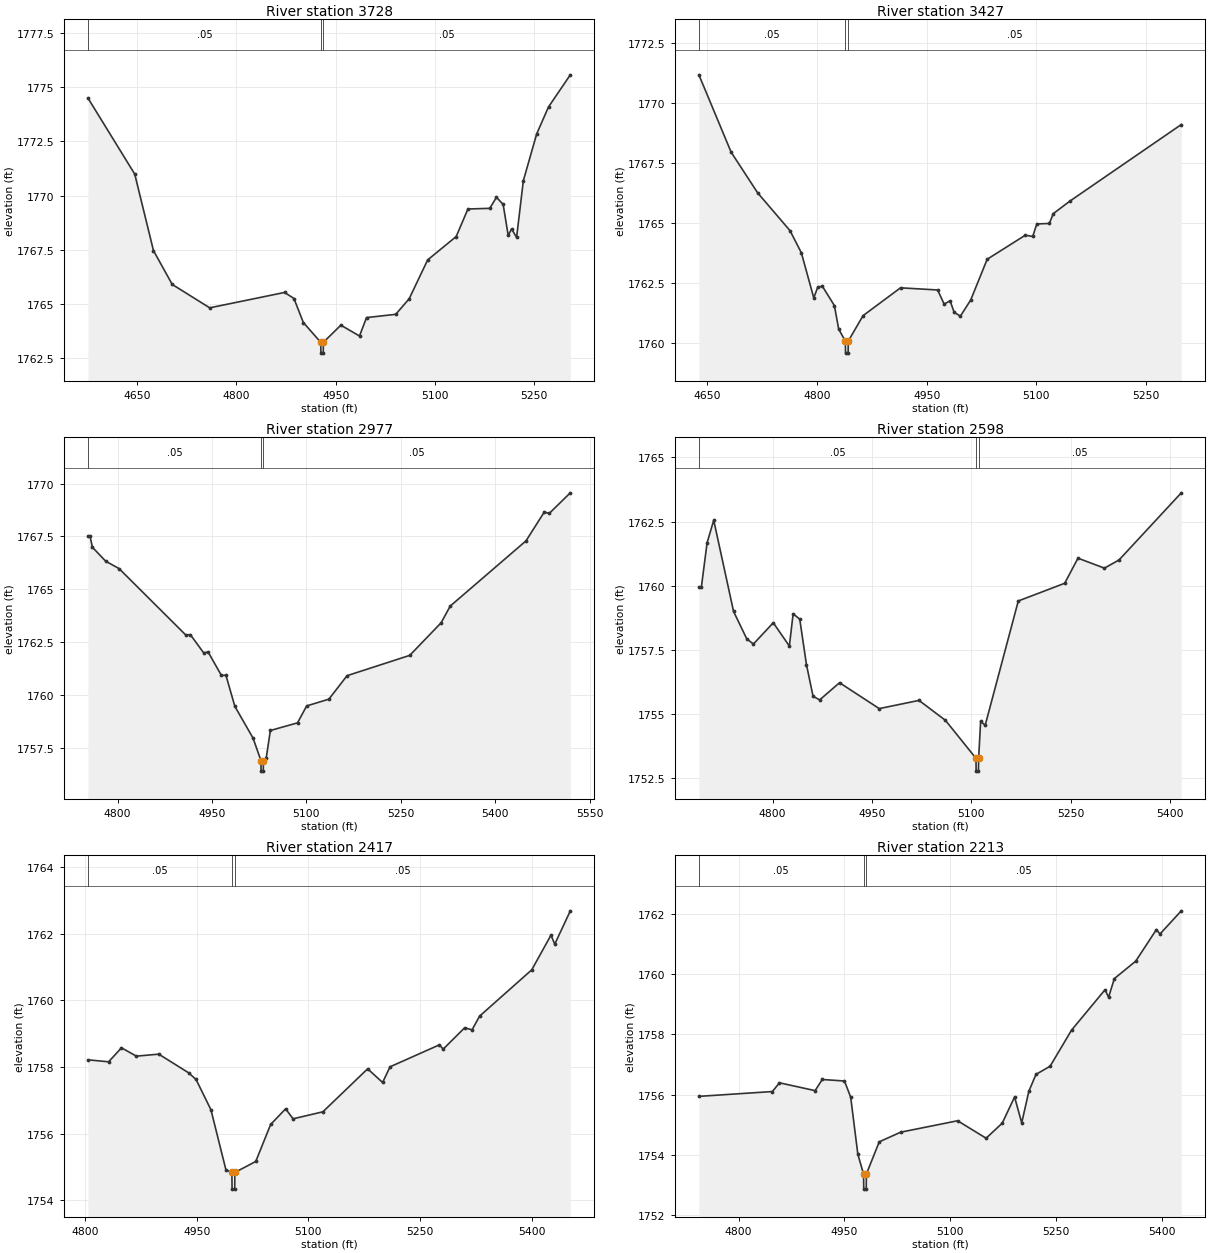
Type RM Length L Ch R = 1,3728,301,301,301
BEGIN DESCRIPTION:
Deadman 28 3.0
END DESCRIPTION:
XS GIS Cut Line= 3
      1658005.01      6926987.99      1657705.00      6927288.00
      1657655.00      6927587.98
#Sta/Elev= 30
  4575.9 1774.50  4646.6 1770.99  4674.9 1767.46  4703.2 1765.90  4759.8 1764.82
  4872.9 1765.53  4887.0 1765.25  4901.2 1764.14  4927.5 1763.23  4927.7 1762.73
  4931.2 1762.73  4931.5 1763.23  4957.8 1764.02  4986.0 1763.52  4996.6 1764.37
  5040.7 1764.52  5061.0 1765.24  5088.9 1767.03  5132.0 1768.11  5149.7 1769.38
  5182.7 1769.41  5192.8 1769.92  5202.9 1769.59  5210.5 1768.16  5215.6 1768.46
  5223.2 1768.07  5233.4 1770.69  5253.6 1772.85  5271.4 1774.09  5304.3 1775.57
#Mann=3,-1,0
  4575.9    0.05       0  4927.5    0.03       0  4931.5    0.05       0
Bank Sta=4927.5,4931.5
Exp/Cntr=0.3,0.1

Type RM Length L Ch R = 1,3427,450,450,450
BEGIN DESCRIPTION:
Mapping XS 673dc59a
END DESCRIPTION:
XS GIS Cut Line= 2
      1657887.35      6926882.70      1657292.66      6927169.19
#Sta/Elev= 30
  4638.3 1771.18  4682.4 1767.96  4718.6 1766.27  4763.0 1764.69  4778.5 1763.77
  4795.5 1761.89  4801.1 1762.35  4807.4 1762.37  4823.7 1761.57  4829.6 1760.59
  4838.7 1760.09  4839.0 1759.59  4842.5 1759.59  4842.7 1760.09  4862.9 1761.15
  4914.2 1762.31  4965.0 1762.22  4973.9 1761.63  4982.0 1761.77  4987.6 1761.29
  4996.1 1761.13  5010.2 1761.80  5032.8 1763.50  5084.9 1764.50  5095.1 1764.45
  5100.7 1764.97  5117.8 1764.99  5123.3 1765.40  5145.9 1765.92  5298.4 1769.11
#Mann=3,-1,0
  4638.3    0.05       0  4838.7    0.03       0  4842.7    0.05       0
Bank Sta=4838.7,4842.7
Exp/Cntr=0.3,0.1

Type RM Length L Ch R = 1,2977,379,379,379
BEGIN DESCRIPTION:
Deadman 28 2.0
END DESCRIPTION:
XS GIS Cut Line= 3
      1657655.00      6926538.00      1657481.87      6926714.17
      1657163.58      6927124.36
#Sta/Elev= 30
  4753.0 1767.50  4756.5 1767.50  4760.1 1766.99  4781.2 1766.33  4802.5 1765.98
  4908.5 1762.84  4915.7 1762.86  4936.8 1762.00  4943.9 1762.04  4965.1 1760.93
  4972.2 1760.94  4986.4 1759.47  5015.3 1757.97  5027.8 1756.91  5028.0 1756.41
  5031.5 1756.41  5031.8 1756.91  5036.1 1757.01  5042.8 1758.33  5085.9 1758.69
  5100.4 1759.49  5135.7 1759.81  5164.6 1760.92  5264.2 1761.88  5314.0 1763.42
  5328.5 1764.21  5448.8 1767.29  5477.8 1768.65  5485.8 1768.59  5519.2 1769.56
#Mann=3,-1,0
  4753.0    0.05       0  5027.8    0.03       0  5031.8    0.05       0
Bank Sta=5027.8,5031.8
Exp/Cntr=0.3,0.1

Type RM Length L Ch R = 1,2598,181,181,181
BEGIN DESCRIPTION:
Mapping XS 5807dcee
END DESCRIPTION:
XS GIS Cut Line= 4
      1657244.94      6926205.65      1657236.26      6926444.35
      1657227.58      6926700.43      1657214.61      6926933.89
#Sta/Elev= 30
  4688.5 1759.93  4692.2 1759.93  4700.9 1761.67  4710.9 1762.55  4740.9 1758.99
  4760.9 1757.92  4770.9 1757.72  4800.9 1758.55  4825.2 1757.64  4830.9 1758.90
  4840.9 1758.69  4851.0 1756.92  4861.0 1755.68  4871.0 1755.54  4901.0 1756.21
  4961.0 1755.20  5021.1 1755.52  5061.1 1754.74  5107.2 1753.26  5107.4 1752.76
  5110.9 1752.76  5111.2 1753.26  5114.2 1754.70  5121.1 1754.55  5171.1 1759.40
  5241.2 1760.09  5261.3 1761.07  5301.3 1760.68  5323.3 1761.00  5417.4 1763.62
#Mann=3,-1,0
  4688.5    0.05       0  5107.2    0.03       0  5111.2    0.05       0
Bank Sta=5107.2,5111.2
Exp/Cntr=0.3,0.1

Type RM Length L Ch R = 1,2417,204,204,204
BEGIN DESCRIPTION:
Mapping XS 666d1101
END DESCRIPTION:
XS GIS Cut Line= 2
      1657101.71      6926223.02      1657058.31      6926869.67
#Sta/Elev= 30
  4803.8 1758.22  4831.6 1758.16  4848.9 1758.58  4868.9 1758.33  4899.0 1758.39
  4939.1 1757.83  4949.1 1757.63  4969.1 1756.72  4989.2 1754.92  4997.2 1754.84
  4997.5 1754.34  5001.0 1754.34  5001.2 1754.84  5029.3 1755.17  5049.3 1756.28
  5069.4 1756.75  5079.4 1756.45  5119.5 1756.66  5179.6 1757.95  5199.7 1757.54
  5209.7 1758.01  5276.1 1758.67  5281.1 1758.54  5309.9 1759.18  5319.9 1759.12
  5330.0 1759.53  5400.1 1760.92  5425.9 1761.96  5431.0 1761.69  5451.9 1762.69
#Mann=3,-1,0
  4803.8    0.05       0  4997.2    0.03       0  5001.2    0.05       0
Bank Sta=4997.2,5001.2
Exp/Cntr=0.3,0.1

Type RM Length L Ch R = 1,2213,549,549,549
BEGIN DESCRIPTION:
Mapping XS bd25718e
END DESCRIPTION:
XS GIS Cut Line= 2
      1656863.00      6926144.88      1656954.15      6926821.97
#Sta/Elev= 30
  4743.9 1755.94  4848.0 1756.10  4858.0 1756.39  4908.5 1756.13  4918.6 1756.50
  4950.1 1756.45  4958.9 1755.91  4969.0 1754.02  4977.1 1753.36  4977.4 1752.86
  4980.9 1752.86  4981.1 1753.36  4999.3 1754.43  5029.6 1754.75  5110.3 1755.13
  5150.7 1754.55  5173.5 1755.05  5191.0 1755.92  5201.1 1755.06  5211.2 1756.11
  5221.3 1756.67  5241.3 1756.94  5271.7 1758.14  5319.1 1759.48  5324.1 1759.23
  5332.3 1759.85  5362.6 1760.43  5391.9 1761.48  5396.9 1761.33  5427.1 1762.10
#Mann=3,-1,0
  4743.9    0.05       0  4977.1    0.03       0  4981.1    0.05       0
Bank Sta=4977.1,4981.1
Exp/Cntr=0.3,0.1

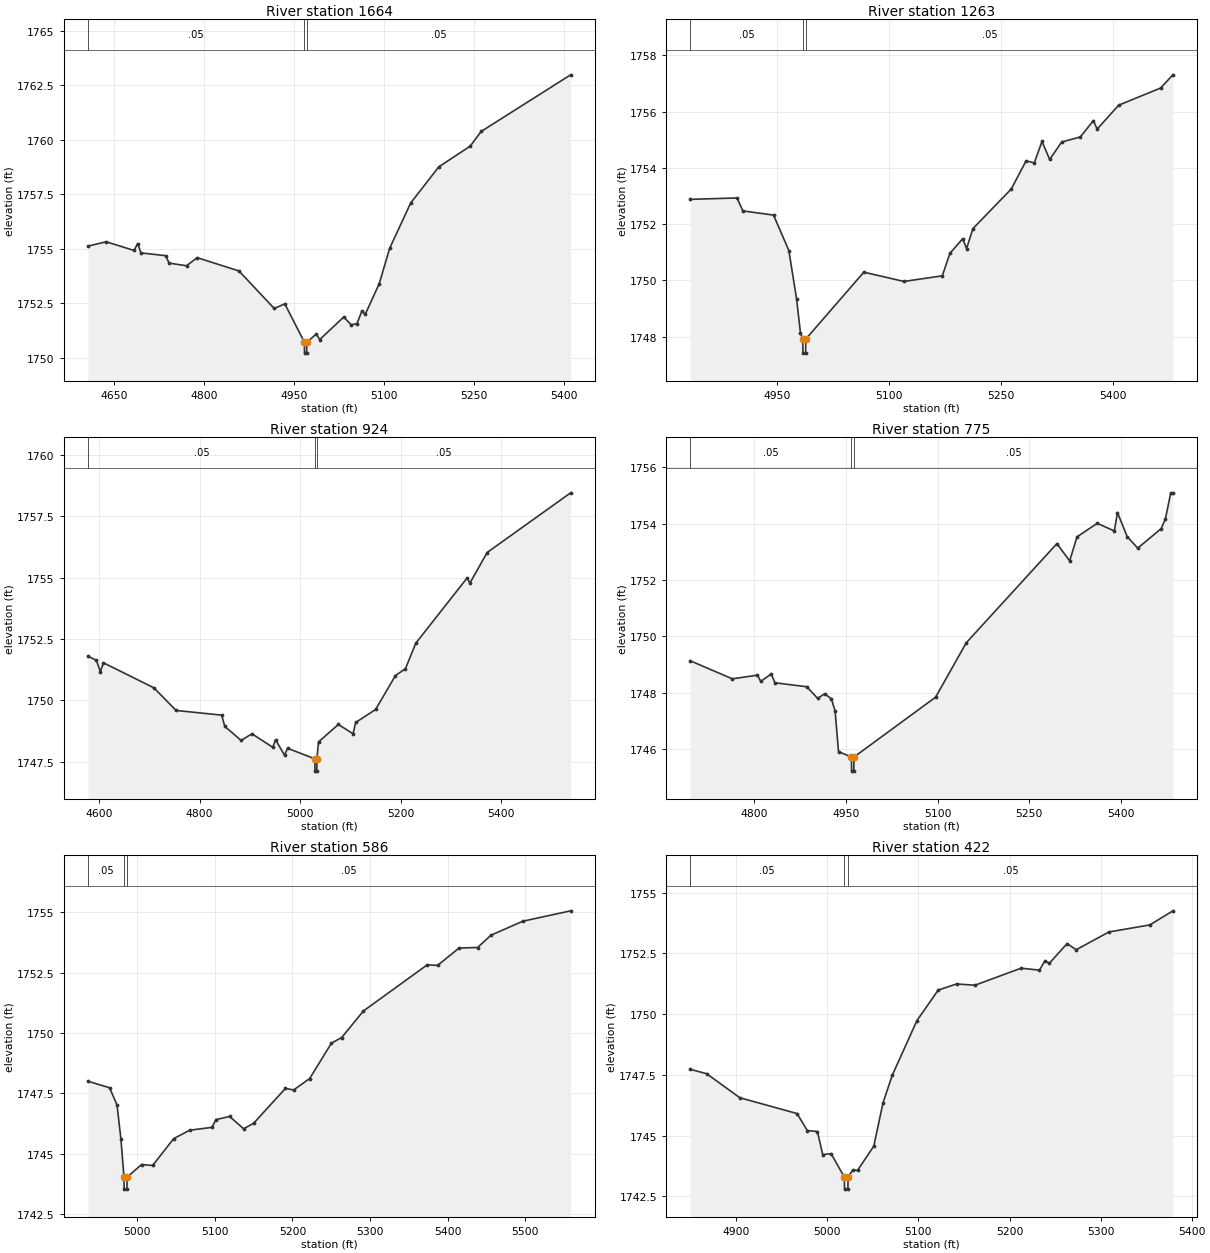
Type RM Length L Ch R = 1,1664,401,401,401
BEGIN DESCRIPTION:
Mapping XS 46b62bae
END DESCRIPTION:
XS GIS Cut Line= 2
      1656763.16      6926127.53      1656442.51      6926864.16
#Sta/Elev= 30
  4607.0 1755.12  4637.4 1755.32  4683.9 1754.92  4689.7 1755.24  4695.2 1754.81
  4736.6 1754.68  4742.0 1754.34  4771.1 1754.22  4788.9 1754.59  4858.4 1753.98
  4917.0 1752.26  4934.7 1752.47  4967.3 1750.71  4967.5 1750.21  4971.0 1750.21
  4971.3 1750.71  4987.3 1751.09  4992.7 1750.83  5032.9 1751.87  5045.0 1751.51
  5054.7 1751.56  5063.0 1752.14  5068.5 1751.99  5091.9 1753.40  5109.2 1755.02
  5144.2 1757.10  5191.1 1758.76  5243.4 1759.71  5261.4 1760.38  5410.4 1762.98
#Mann=3,-1,0
  4607.0    0.05       0  4967.3    0.03       0  4971.3    0.05       0
Bank Sta=4967.3,4971.3
Exp/Cntr=0.3,0.1

Type RM Length L Ch R = 1,1263,339,339,339
BEGIN DESCRIPTION:
Mapping XS 31abf305
END DESCRIPTION:
XS GIS Cut Line= 2
      1656463.70      6926049.36      1656316.13      6926678.69
#Sta/Elev= 30
  4834.1 1752.88  4896.8 1752.93  4904.6 1752.47  4945.7 1752.32  4966.2 1751.06
  4976.5 1749.35  4981.7 1748.14  4984.8 1747.91  4985.1 1747.41  4988.6 1747.41
  4988.9 1747.91  5066.6 1750.29  5120.3 1749.96  5171.7 1750.16  5181.9 1750.96
  5199.0 1751.48  5204.2 1751.13  5212.7 1751.84  5264.1 1753.25  5283.9 1754.25
  5294.9 1754.18  5305.2 1754.94  5315.5 1754.30  5331.5 1754.92  5356.5 1755.10
  5374.0 1755.68  5379.1 1755.38  5407.9 1756.23  5464.0 1756.84  5480.5 1757.31
#Mann=3,-1,0
  4834.1    0.05       0  4984.8    0.03       0  4988.9    0.05       0
Bank Sta=4984.8,4988.9
Exp/Cntr=0.3,0.1

Type RM Length L Ch R = 1,924,149,149,149
BEGIN DESCRIPTION:
Mapping XS 713fa1e8
END DESCRIPTION:
XS GIS Cut Line= 4
      1656378.54      6925957.38      1656231.06      6926065.00
      1656135.40      6926300.19      1655996.35      6926804.71
#Sta/Elev= 30
  4578.1 1751.80  4594.9 1751.63  4602.8 1751.17  4609.0 1751.53  4709.4 1750.51
  4753.4 1749.59  4844.0 1749.40  4850.3 1748.94  4882.7 1748.37  4904.3 1748.64
  4945.7 1748.09  4951.1 1748.40  4969.0 1747.77  4975.1 1748.05  5029.3 1747.62
  5029.6 1747.12  5033.2 1747.12  5033.4 1747.62  5036.6 1748.31  5076.1 1749.02
  5105.3 1748.64  5110.5 1749.10  5150.1 1749.63  5189.6 1751.01  5209.4 1751.29
  5230.1 1752.33  5332.3 1754.99  5337.5 1754.77  5371.9 1756.02  5537.9 1758.45
#Mann=3,-1,0
  4578.1    0.05       0  5029.3    0.03       0  5033.4    0.05       0
Bank Sta=5029.3,5033.4
Exp/Cntr=0.3,0.1

Type RM Length L Ch R = 1,775,189,189,189
BEGIN DESCRIPTION:
Mapping XS 938751ee
END DESCRIPTION:
XS GIS Cut Line= 3
      1656146.65      6925926.99      1656023.80      6926202.91
      1655883.96      6926669.68
#Sta/Elev= 30
  4695.6 1749.14  4764.5 1748.50  4805.5 1748.63  4811.0 1748.41  4828.1 1748.67
  4834.2 1748.36  4886.2 1748.22  4903.9 1747.81  4915.6 1747.97  4926.6 1747.79
  4932.6 1747.35  4938.1 1745.92  4959.3 1745.73  4959.5 1745.23  4963.1 1745.23
  4963.4 1745.73  5096.9 1747.85  5147.1 1749.78  5295.2 1753.29  5316.1 1752.68
  5328.1 1753.53  5361.2 1754.01  5389.1 1753.74  5394.3 1754.39  5410.1 1753.54
  5427.4 1753.13  5465.7 1753.82  5472.7 1754.17  5481.4 1755.09  5484.9 1755.09
#Mann=3,-1,0
  4695.6    0.05       0  4959.3    0.03       0  4963.4    0.05       0
Bank Sta=4959.3,4963.4
Exp/Cntr=0.3,0.1

Type RM Length L Ch R = 1,586,164,164,164
BEGIN DESCRIPTION:
Mapping XS 493c1d52
END DESCRIPTION:
XS GIS Cut Line= 3
      1655889.63      6926030.97      1655953.88      6926282.28
      1655865.40      6926634.34
#Sta/Elev= 30
  4936.3 1748.00  4964.2 1747.73  4973.8 1747.02  4978.9 1745.59  4982.8 1744.03
  4983.0 1743.53  4986.6 1743.53  4986.9 1744.03  5005.5 1744.55  5019.8 1744.51
  5046.8 1745.62  5067.4 1745.97  5096.3 1746.09  5101.4 1746.41  5119.0 1746.54
  5137.1 1746.03  5150.0 1746.26  5190.9 1747.70  5201.6 1747.64  5222.2 1748.11
  5250.3 1749.58  5263.5 1749.81  5291.5 1750.91  5373.7 1752.82  5387.2 1752.80
  5414.9 1753.52  5438.7 1753.54  5456.0 1754.05  5497.1 1754.63  5558.7 1755.06
#Mann=3,-1,0
  4936.3    0.05       0  4982.8    0.03       0  4986.9    0.05       0
Bank Sta=4982.8,4986.9
Exp/Cntr=0.3,0.1

Type RM Length L Ch R = 1,422,0,0,0
BEGIN DESCRIPTION:
Deadman 28 1.0
END DESCRIPTION:
XS GIS Cut Line= 3
      1655842.38      6926051.74      1655776.24      6926191.57
      1655830.00      6926563.02
#Sta/Elev= 30
  4849.4 1747.73  4867.4 1747.55  4903.9 1746.56  4966.7 1745.91  4978.0 1745.21
  4989.1 1745.17  4994.9 1744.22  5004.1 1744.26  5018.6 1743.30  5018.9 1742.80
  5022.5 1742.80  5022.8 1743.30  5028.0 1743.59  5033.1 1743.57  5051.0 1744.57
  5061.1 1746.35  5071.2 1747.48  5098.3 1749.73  5121.7 1750.99  5141.9 1751.24
  5162.1 1751.19  5212.7 1751.89  5232.9 1751.81  5238.8 1752.19  5243.9 1752.10
  5263.2 1752.90  5273.3 1752.65  5309.1 1753.38  5354.1 1753.67  5379.4 1754.25
#Mann=3,-1,0
  4849.4    0.05       0  5018.6    0.03       0  5022.8    0.05       0
Bank Sta=5018.6,5022.8
Exp/Cntr=0.3,0.1

Chan Stop Cuts=-1