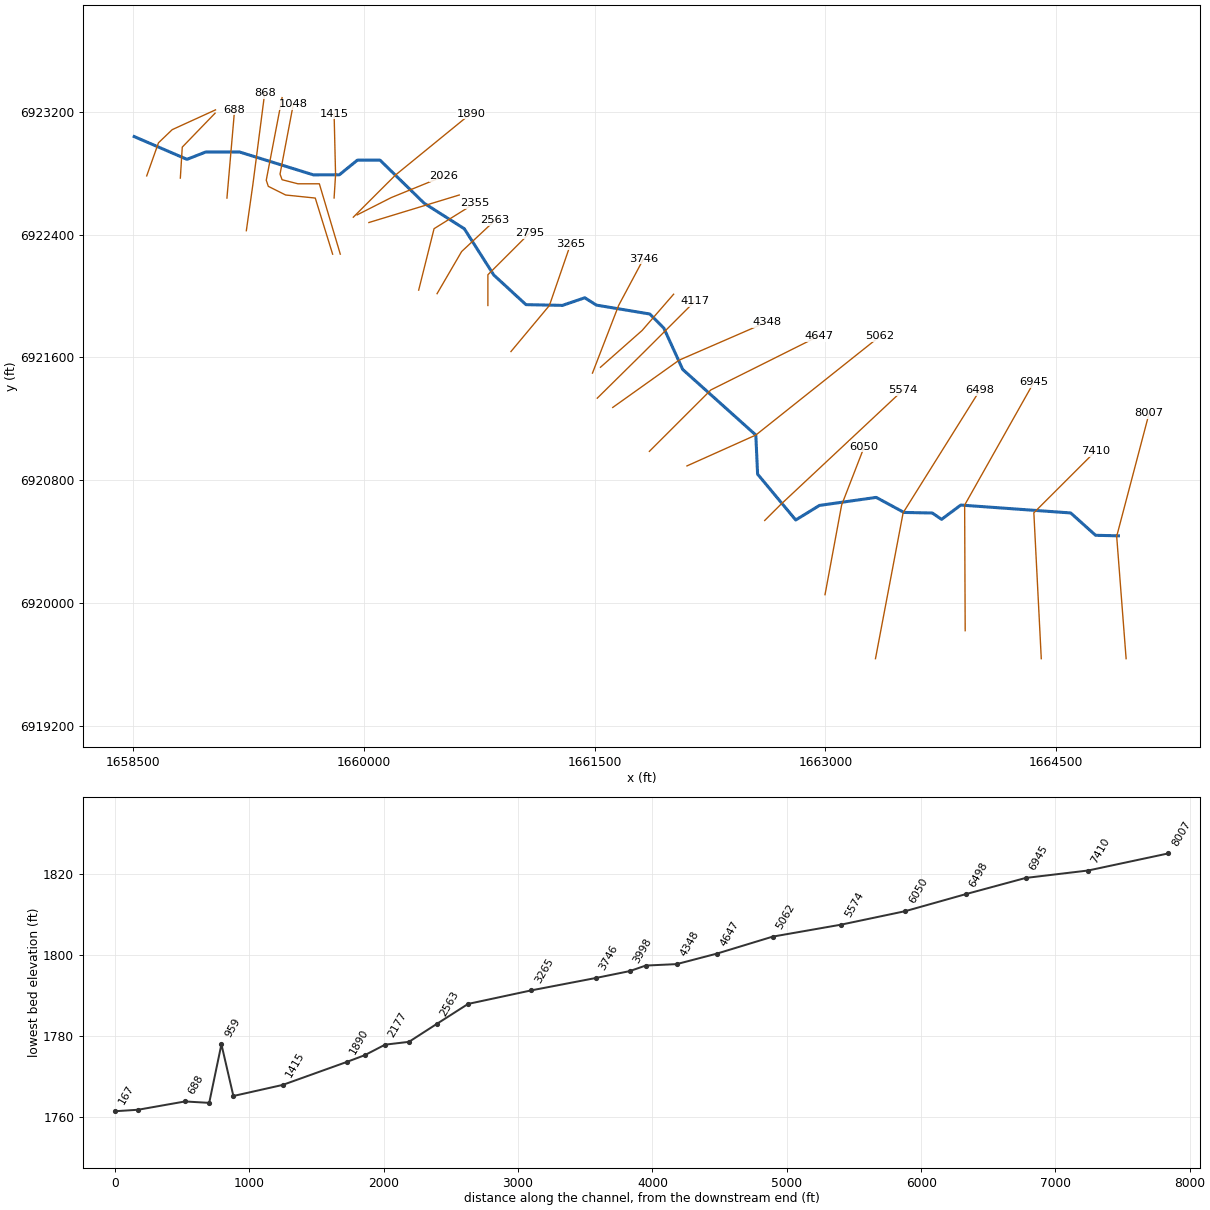
--- Deadman 29.prj (project) ---

Proj Title=Deadman 29 Base Level Engineering
Current Plan=p01
Default Exp/Contr=0.3,0.1
English Units
Geom File=g01
Flow File=f01
Plan File=p01
BEGIN DESCRIPTION:
Deadman 29
END DESCRIPTION:

--- Deadman 29.p01 (plan) ---

Plan Title=Multiple Run
Short Identifier=Multiple
Geom File=g01
Flow File=f01
Subcritical Flow
K Sum by GR= 0
Std Step Tol= 0.01
Critical Tol= 0.01
Num of Std Step Trials= 20
Max Error Tol= 0.3
Flow Tol Ratio= 0.001
Split Flow NTrial= 30
Split Flow Tol= 0.02
Split Flow Ratio= 0.02
Log Output Level= 0
Friction Slope Method= 1
Unsteady Friction Slope Method= 2
Unsteady Bridges Friction Slope Method= 1
Parabolic Critical Depth
Global Vel Dist=  1 , 1 , 1
Global Log Level= 0
CheckData=True
Encroach Param= -1, 0, 0, 0
BEGIN DESCRIPTION:
Multiple Run
END DESCRIPTION:

--- Deadman 29.f01 (steady flow) ---

Flow Title=Multiple
Number of Profiles=7
Profile Names=10-year,25-year,50-year,1pct_min,100-year,1pct_plu,500-year
River Rch & RM= Deadman 29,Reach-1,8007
     251     346     425     260     520    1037     785
River Rch & RM= Deadman 29,Reach-1,7410
     397     563     704     438     873    1743    1363
River Rch & RM= Deadman 29,Reach-1,688
     406     578     723     450     898    1792    1406
Boundary for River Rch & Prof#=Deadman 29,Reach-1,1
Up Type=0
Dn Type=3
Dn Slope=0.005
Boundary for River Rch & Prof#=Deadman 29,Reach-1,2
Up Type=0
Dn Type=3
Dn Slope=0.005
Boundary for River Rch & Prof#=Deadman 29,Reach-1,3
Up Type=0
Dn Type=3
Dn Slope=0.005
Boundary for River Rch & Prof#=Deadman 29,Reach-1,4
Up Type=0
Dn Type=3
Dn Slope=0.005
Boundary for River Rch & Prof#=Deadman 29,Reach-1,5
Up Type=0
Dn Type=3
Dn Slope=0.005
Boundary for River Rch & Prof#=Deadman 29,Reach-1,6
Up Type=0
Dn Type=3
Dn Slope=0.005
Boundary for River Rch & Prof#=Deadman 29,Reach-1,7
Up Type=0
Dn Type=3
Dn Slope=0.005

--- Deadman 29.g01 (geometry) ---

Geom Title=Existing Conditions

River Reach=Deadman 29,Reach-1
Reach XY= 30
      1664905.00      6920438.00      1664756.45      6920441.50
      1664594.57      6920586.95      1663879.88      6920638.29
      1663755.10      6920545.33      1663694.57      6920586.61
      1663510.93      6920590.24      1663330.08      6920688.24
      1662960.86      6920635.93      1662806.65      6920541.10
      1662558.75      6920839.55      1662547.19      6921094.19
      1662071.70      6921521.51      1661949.18      6921790.31
      1661857.44      6921882.48      1661510.94      6921940.26
      1661434.90      6921988.09      1661289.78      6921938.52
      1661052.55      6921943.46      1660843.25      6922136.34
      1660651.70      6922437.60      1660390.55      6922603.78
      1660103.53      6922884.47      1659956.53      6922884.27
      1659839.06      6922788.92      1659670.22      6922788.52
      1659189.78      6922937.48      1658970.16      6922937.34
      1658848.28      6922889.51      1658505.00      6923038.00

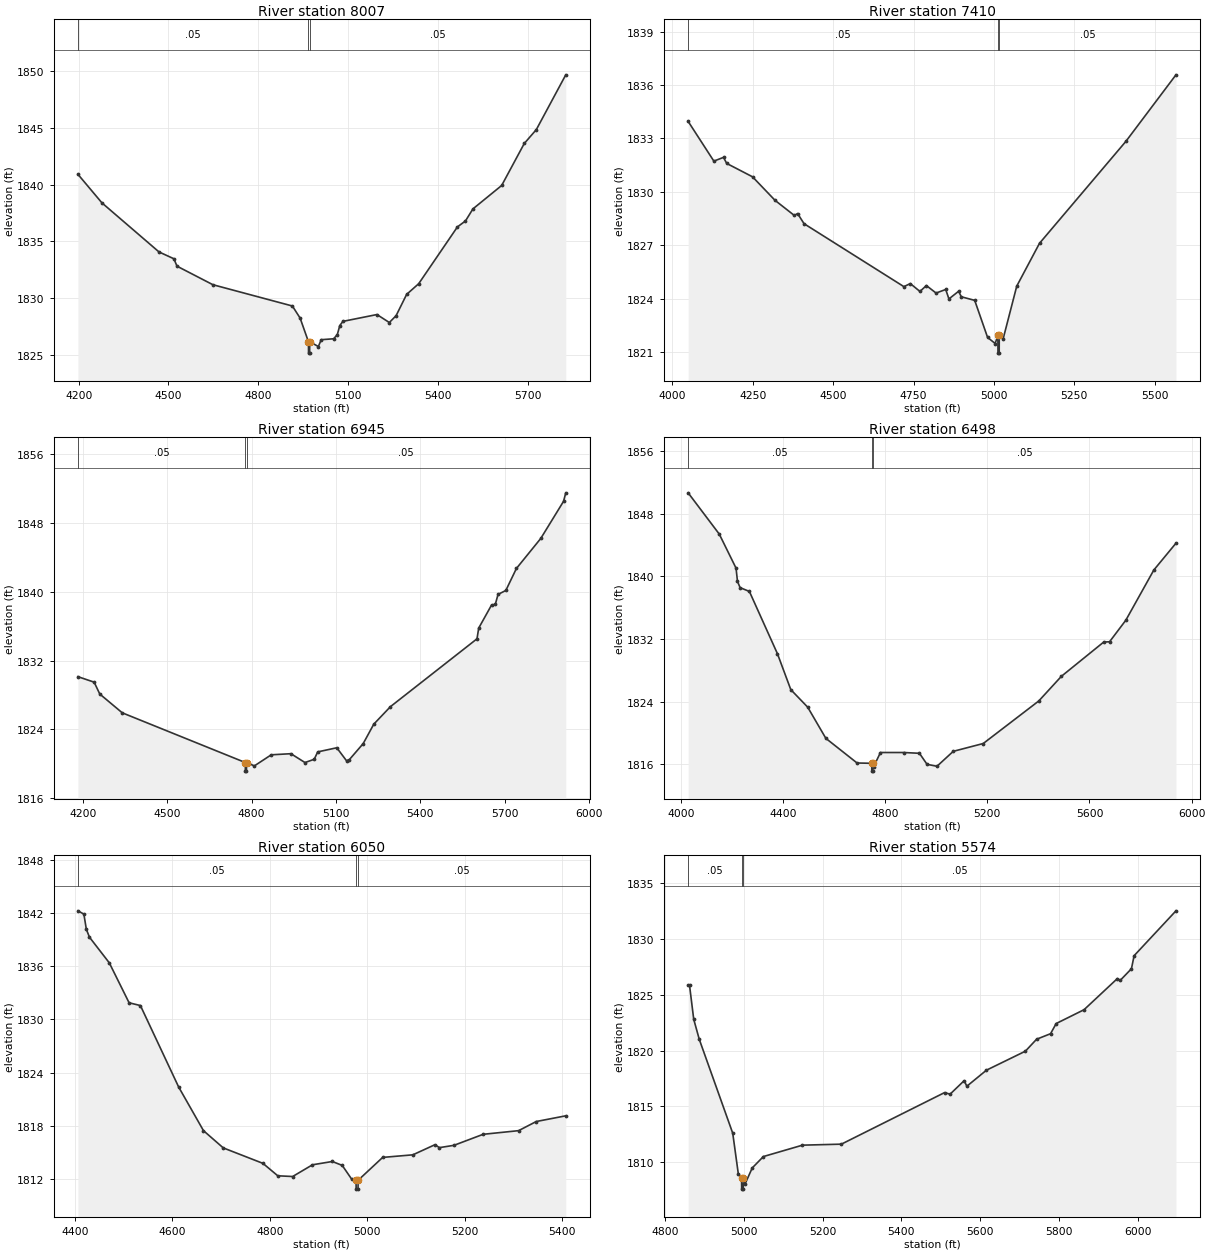
Type RM Length L Ch R = 1,8007,597,597,597
BEGIN DESCRIPTION:
Deadman 29 17.0
END DESCRIPTION:
XS GIS Cut Line= 3
      1664955.00      6919638.03      1664893.61      6920434.49
      1665105.01      6921238.03
#Sta/Elev= 30
  4197.6 1840.90  4277.8 1838.39  4468.4 1834.08  4518.2 1833.48  4528.5 1832.83
  4648.5 1831.20  4914.0 1829.33  4939.8 1828.27  4967.7 1826.19  4968.0 1825.19
  4971.6 1825.19  4971.9 1826.19  5000.8 1825.77  5010.4 1826.37  5051.7 1826.45
  5064.0 1826.81  5072.4 1827.61  5082.8 1827.98  5196.5 1828.58  5237.9 1827.88
  5260.5 1828.48  5295.7 1830.35  5336.0 1831.29  5465.4 1836.28  5492.2 1836.80
  5517.1 1837.86  5613.2 1839.92  5688.7 1843.61  5729.0 1844.83  5827.3 1849.64
#Mann=3,-1,0
  4197.6    0.05       0  4967.7    0.03       0  4971.9    0.05       0
Bank Sta=4967.7,4971.9
Exp/Cntr=0.3,0.1

Type RM Length L Ch R = 1,7410,465,465,465
BEGIN DESCRIPTION:
Deadman 29 16.0
END DESCRIPTION:
XS GIS Cut Line= 3
      1664403.35      6919638.11      1664355.00      6920588.00
      1664755.00      6920988.00
#Sta/Elev= 30
  4049.2 1833.96  4129.2 1831.73  4159.2 1831.94  4169.2 1831.60  4249.4 1830.85
  4319.4 1829.53  4379.5 1828.68  4389.5 1828.79  4409.6 1828.22  4720.0 1824.69
  4740.0 1824.86  4770.0 1824.42  4790.0 1824.75  4820.1 1824.33  4850.1 1824.53
  4860.1 1824.00  4890.2 1824.43  4898.6 1824.12  4940.2 1823.92  4980.3 1821.84
  5003.9 1821.50  5012.3 1821.96  5012.6 1820.96  5016.3 1820.96  5016.6 1821.96
  5028.6 1821.76  5071.0 1824.72  5141.7 1827.12  5410.4 1832.84  5566.0 1836.57
#Mann=3,-1,0
  4049.2    0.05       0  5012.3    0.05       0  5016.6    0.05       0
Bank Sta=5012.3,5016.6
Exp/Cntr=0.3,0.1

Type RM Length L Ch R = 1,6945,447,447,447
BEGIN DESCRIPTION:
Deadman 29 15.0
END DESCRIPTION:
XS GIS Cut Line= 3
      1663908.56      6919820.35      1663905.00      6920638.00
      1664354.98      6921437.97
#Sta/Elev= 30
  4182.1 1830.12  4239.8 1829.48  4259.8 1828.10  4339.8 1825.91  4777.6 1820.12
  4777.9 1819.12  4781.6 1819.12  4781.9 1820.12  4809.8 1819.73  4869.8 1821.02
  4939.8 1821.15  4989.8 1820.12  5022.7 1820.50  5035.1 1821.36  5103.0 1821.84
  5137.8 1820.32  5148.0 1820.47  5197.0 1822.33  5234.6 1824.59  5293.9 1826.63
  5601.8 1834.53  5607.9 1835.78  5653.7 1838.47  5666.8 1838.53  5676.7 1839.70
  5704.4 1840.16  5742.0 1842.72  5828.7 1846.22  5909.7 1850.54  5917.6 1851.53
#Mann=3,-1,0
  4182.1    0.05       0  4777.6    0.03       0  4781.9    0.05       0
Bank Sta=4777.6,4781.9
Exp/Cntr=0.3,0.1

Type RM Length L Ch R = 1,6498,448,448,448
BEGIN DESCRIPTION:
Deadman 29 14.0
END DESCRIPTION:
XS GIS Cut Line= 3
      1663325.23      6919638.08      1663505.00      6920588.00
      1664005.01      6921388.02
#Sta/Elev= 30
  4028.4 1850.68  4150.4 1845.40  4216.0 1841.05  4221.7 1839.35  4231.9 1838.56
  4268.3 1838.07  4378.1 1830.11  4430.4 1825.52  4496.5 1823.28  4567.7 1819.29
  4689.9 1816.14  4747.4 1816.10  4747.7 1815.10  4751.4 1815.10  4751.7 1816.10
  4754.6 1815.66  4781.5 1817.48  4873.0 1817.48  4934.1 1817.38  4963.9 1815.97
  5002.8 1815.72  5066.5 1817.63  5183.9 1818.63  5401.4 1824.07  5489.9 1827.22
  5655.6 1831.60  5678.6 1831.64  5742.2 1834.39  5851.9 1840.81  5938.6 1844.24
#Mann=3,-1,0
  4028.4    0.05       0  4747.4    0.03       0  4751.7    0.05       0
Bank Sta=4747.4,4751.7
Exp/Cntr=0.3,0.1

Type RM Length L Ch R = 1,6050,476,476,476
BEGIN DESCRIPTION:
Deadman 29 13.0
END DESCRIPTION:
XS GIS Cut Line= 3
      1662997.10      6920054.73      1663105.00      6920638.00
      1663252.31      6921018.30
#Sta/Elev= 30
  4406.3 1842.23  4418.5 1841.86  4423.6 1840.14  4430.0 1839.26  4470.6 1836.38
  4511.3 1831.88  4534.5 1831.57  4613.0 1822.40  4663.9 1817.49  4704.5 1815.55
  4785.9 1813.81  4816.4 1812.41  4846.9 1812.33  4887.6 1813.65  4928.3 1814.02
  4948.6 1813.58  4967.9 1812.04  4977.0 1811.91  4977.2 1810.91  4981.0 1810.91
  4981.3 1811.91  5031.6 1814.48  5093.5 1814.77  5138.9 1815.91  5148.0 1815.58
  5177.9 1815.84  5237.8 1817.08  5310.5 1817.49  5346.8 1818.52  5407.3 1819.16
#Mann=3,-1,0
  4406.3    0.05       0  4977.0    0.03       0  4981.3    0.05       0
Bank Sta=4977,4981.3
Exp/Cntr=0.3,0.1

Type RM Length L Ch R = 1,5574,512,512,512
BEGIN DESCRIPTION:
Deadman 29 12.0
END DESCRIPTION:
XS GIS Cut Line= 3
      1662604.98      6920537.98      1662705.00      6920638.00
      1663504.97      6921387.97
#Sta/Elev= 30
  4858.7 1825.83  4862.3 1825.83  4872.9 1822.80  4887.0 1821.00  4971.9 1812.59
  4986.0 1808.96  4994.3 1808.58  4994.6 1807.58  4998.6 1807.58  4998.9 1808.58
  5003.6 1808.08  5021.4 1809.48  5049.7 1810.50  5148.9 1811.52  5247.6 1811.61
  5509.4 1816.23  5523.5 1816.09  5559.2 1817.30  5566.0 1816.80  5615.8 1818.24
  5714.5 1819.94  5742.9 1821.01  5778.5 1821.51  5792.7 1822.42  5863.5 1823.66
  5948.0 1826.45  5955.3 1826.29  5983.7 1827.33  5990.5 1828.50  6096.7 1832.52
#Mann=3,-1,0
  4858.7    0.05       0  4994.3    0.05       0  4998.9    0.05       0
Bank Sta=4994.3,4998.9
Exp/Cntr=0.3,0.1

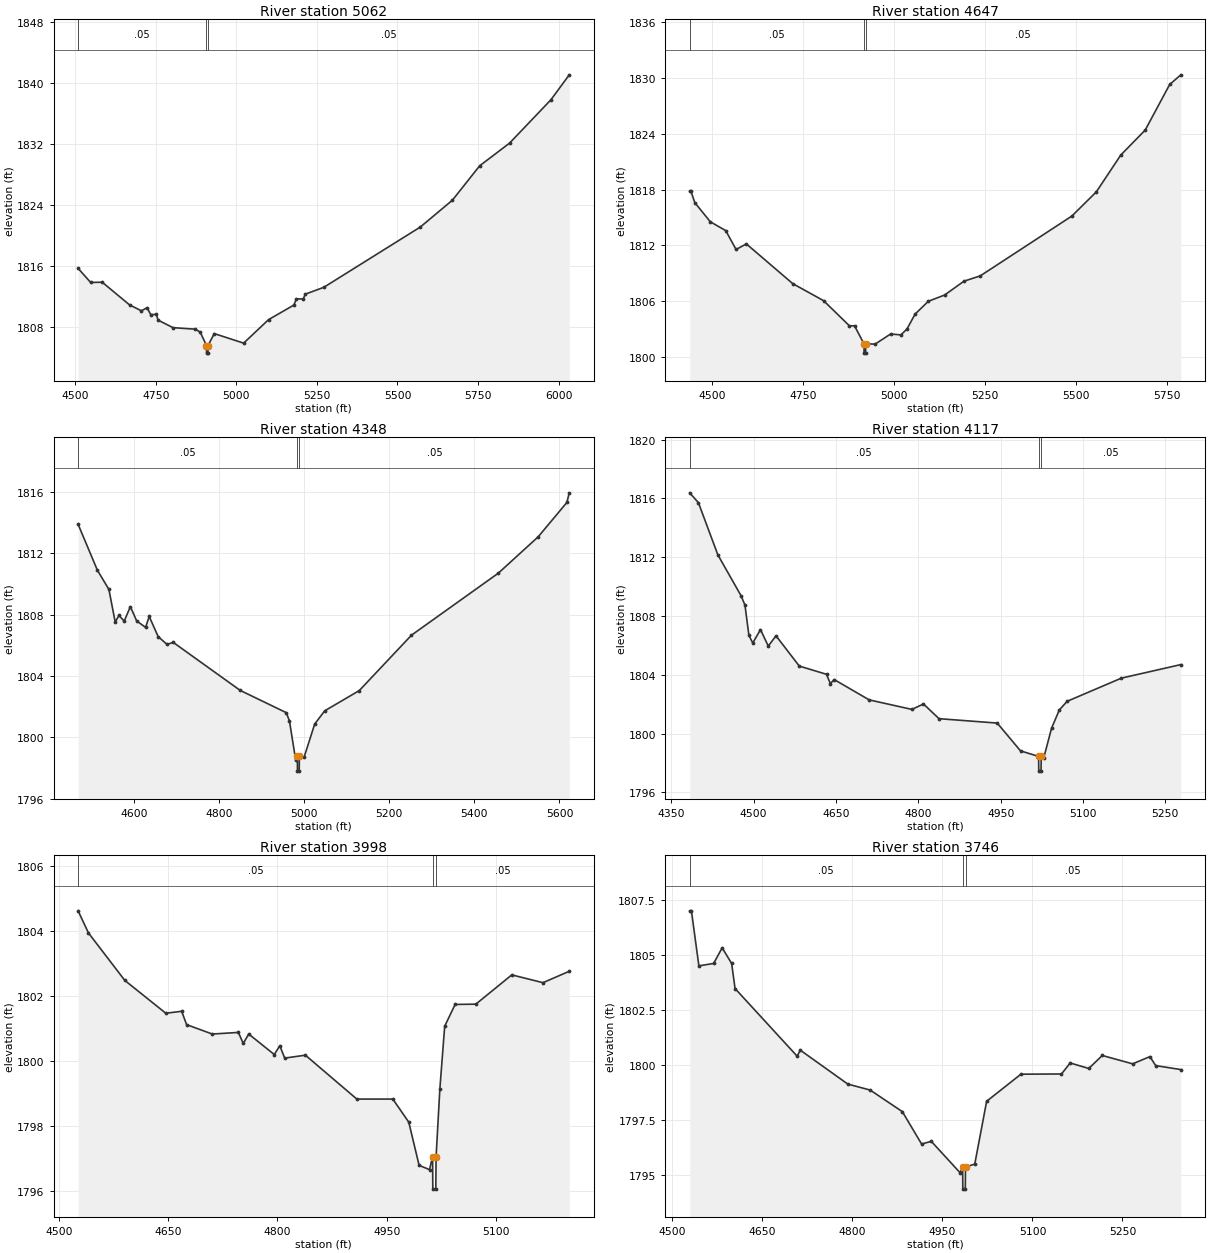
Type RM Length L Ch R = 1,5062,415,415,415
BEGIN DESCRIPTION:
Deadman 29 11.0
END DESCRIPTION:
XS GIS Cut Line= 3
      1662099.50      6920893.28      1662547.19      6921094.19
      1663355.02      6921738.01
#Sta/Elev= 30
  4509.3 1815.72  4548.2 1813.87  4584.2 1813.90  4668.8 1810.93  4705.6 1810.15
  4723.3 1810.56  4734.5 1809.65  4751.9 1809.68  4757.4 1808.93  4803.7 1807.94
  4873.3 1807.74  4888.0 1807.36  4907.6 1805.60  4907.9 1804.60  4911.9 1804.60
  4912.3 1805.60  4931.8 1807.16  5022.8 1805.91  5100.1 1808.99  5178.6 1810.90
  5186.6 1811.72  5207.4 1811.70  5214.6 1812.34  5271.5 1813.23  5571.0 1821.14
  5670.3 1824.65  5755.1 1829.17  5848.0 1832.15  5976.1 1837.83  6033.0 1841.10
#Mann=3,-1,0
  4509.3    0.05       0  4907.6    0.05       0  4912.3    0.05       0
Bank Sta=4907.6,4912.3
Exp/Cntr=0.3,0.1

Type RM Length L Ch R = 1,4647,299,299,299
BEGIN DESCRIPTION:
Deadman 29 10.0
END DESCRIPTION:
XS GIS Cut Line= 3
      1661855.00      6920988.00      1662255.00      6921388.00
      1662954.99      6921738.00
#Sta/Elev= 30
  4439.5 1817.81  4443.0 1817.81  4453.6 1816.59  4496.1 1814.53  4538.5 1813.58
  4566.8 1811.55  4595.1 1812.15  4722.3 1807.88  4807.2 1806.04  4877.9 1803.34
  4892.0 1803.34  4917.9 1801.40  4918.3 1800.40  4922.4 1800.40  4922.7 1801.40
  4948.6 1801.37  4991.0 1802.46  5019.2 1802.36  5035.9 1802.99  5058.3 1804.60
  5094.6 1805.98  5139.3 1806.65  5192.5 1808.14  5237.2 1808.71  5488.7 1815.15
  5555.8 1817.75  5622.9 1821.71  5690.0 1824.40  5757.1 1829.30  5787.8 1830.34
#Mann=3,-1,0
  4439.5    0.05       0  4917.9    0.05       0  4922.7    0.05       0
Bank Sta=4917.9,4922.7
Exp/Cntr=0.3,0.1

Type RM Length L Ch R = 1,4348,231,231,231
BEGIN DESCRIPTION:
Deadman 29 9.0
END DESCRIPTION:
XS GIS Cut Line= 3
      1661616.82      6921273.95      1662048.95      6921582.20
      1662620.22      6921830.73
#Sta/Elev= 30
  4469.2 1813.89  4514.6 1810.89  4541.6 1809.64  4556.4 1807.51  4565.0 1807.95
  4577.5 1807.58  4592.0 1808.52  4606.8 1807.59  4627.7 1807.17  4636.3 1807.88
  4657.2 1806.57  4678.1 1806.06  4692.8 1806.19  4850.1 1803.06  4958.3 1801.61
  4965.7 1801.07  4980.4 1798.51  4984.2 1798.80  4984.5 1797.80  4988.6 1797.80
  4989.0 1798.80  5000.0 1798.70  5025.0 1800.87  5048.5 1801.73  5129.7 1803.05
  5252.3 1806.66  5456.2 1810.70  5549.9 1813.07  5617.3 1815.31  5623.0 1815.94
#Mann=3,-1,0
  4469.2    0.05       0  4984.2    0.05       0  4989.0    0.05       0
Bank Sta=4984.2,4989
Exp/Cntr=0.3,0.1

Type RM Length L Ch R = 1,4117,119,119,119
BEGIN DESCRIPTION:
Mapping XS 60887a5b
END DESCRIPTION:
XS GIS Cut Line= 3
      1661516.22      6921334.29      1661811.34      6921625.94
      1662150.81      6921965.41
#Sta/Elev= 30
  4383.4 1816.38  4399.3 1815.71  4434.7 1812.16  4477.1 1809.37  4484.1 1808.74
  4491.3 1806.68  4498.3 1806.16  4512.4 1807.07  4526.6 1805.95  4540.7 1806.65
  4583.1 1804.59  4632.7 1804.03  4639.7 1803.40  4646.8 1803.67  4710.4 1802.29
  4788.3 1801.64  4809.4 1802.01  4837.7 1801.01  4943.8 1800.71  4986.2 1798.82
  5019.2 1798.44  5019.5 1797.44  5023.6 1797.44  5024.0 1798.44  5028.6 1798.35
  5042.8 1800.36  5056.9 1801.60  5071.1 1802.19  5170.1 1803.77  5278.4 1804.69
#Mann=3,-1,0
  4383.4    0.05       0  5019.2    0.03       0  5024.0    0.05       0
Bank Sta=5019.2,5024
Exp/Cntr=0.3,0.1

Type RM Length L Ch R = 1,3998,252,252,252
BEGIN DESCRIPTION:
Mapping XS cdb45d58
END DESCRIPTION:
XS GIS Cut Line= 3
      1661537.03      6921535.65      1661807.87      6921775.24
      1662012.73      6922011.35
#Sta/Elev= 30
  4526.3 1804.63  4540.5 1803.95  4590.4 1802.49  4646.7 1801.48  4668.5 1801.54
  4675.2 1801.13  4710.5 1800.84  4746.3 1800.89  4753.0 1800.55  4760.5 1800.84
  4795.6 1800.21  4803.2 1800.48  4809.9 1800.10  4838.3 1800.19  4908.9 1798.84
  4958.3 1798.84  4980.2 1798.13  4994.4 1796.80  5008.7 1796.67  5012.9 1797.07
  5013.2 1796.07  5017.3 1796.07  5017.7 1797.07  5022.9 1799.16  5029.5 1801.08
  5043.8 1801.75  5072.3 1801.76  5121.6 1802.66  5164.4 1802.42  5200.5 1802.77
#Mann=3,-1,0
  4526.3    0.05       0  5012.9    0.05       0  5017.7    0.05       0
Bank Sta=5012.9,5017.7
Exp/Cntr=0.3,0.1

Type RM Length L Ch R = 1,3746,481,481,481
BEGIN DESCRIPTION:
Deadman 29 8.0
END DESCRIPTION:
XS GIS Cut Line= 3
      1661484.97      6921497.50      1661655.00      6921938.00
      1661818.00      6922243.46
#Sta/Elev= 30
  4528.9 1807.01  4531.8 1807.01  4544.2 1804.51  4568.8 1804.62  4583.0 1805.33
  4598.8 1804.62  4604.5 1803.48  4707.9 1800.41  4713.3 1800.68  4792.4 1799.14
  4829.6 1798.87  4883.2 1797.89  4915.3 1796.42  4931.5 1796.54  4979.6 1795.11
  4983.7 1795.37  4984.0 1794.37  4988.1 1794.37  4988.5 1795.37  5003.9 1795.51
  5023.7 1798.36  5080.8 1799.59  5148.4 1799.60  5162.9 1800.10  5193.8 1799.85
  5216.4 1800.44  5267.0 1800.06  5295.8 1800.39  5305.3 1799.98  5347.3 1799.80
#Mann=3,-1,0
  4528.9    0.05       0  4983.7    0.03       0  4988.5    0.05       0
Bank Sta=4983.7,4988.5
Exp/Cntr=0.3,0.1

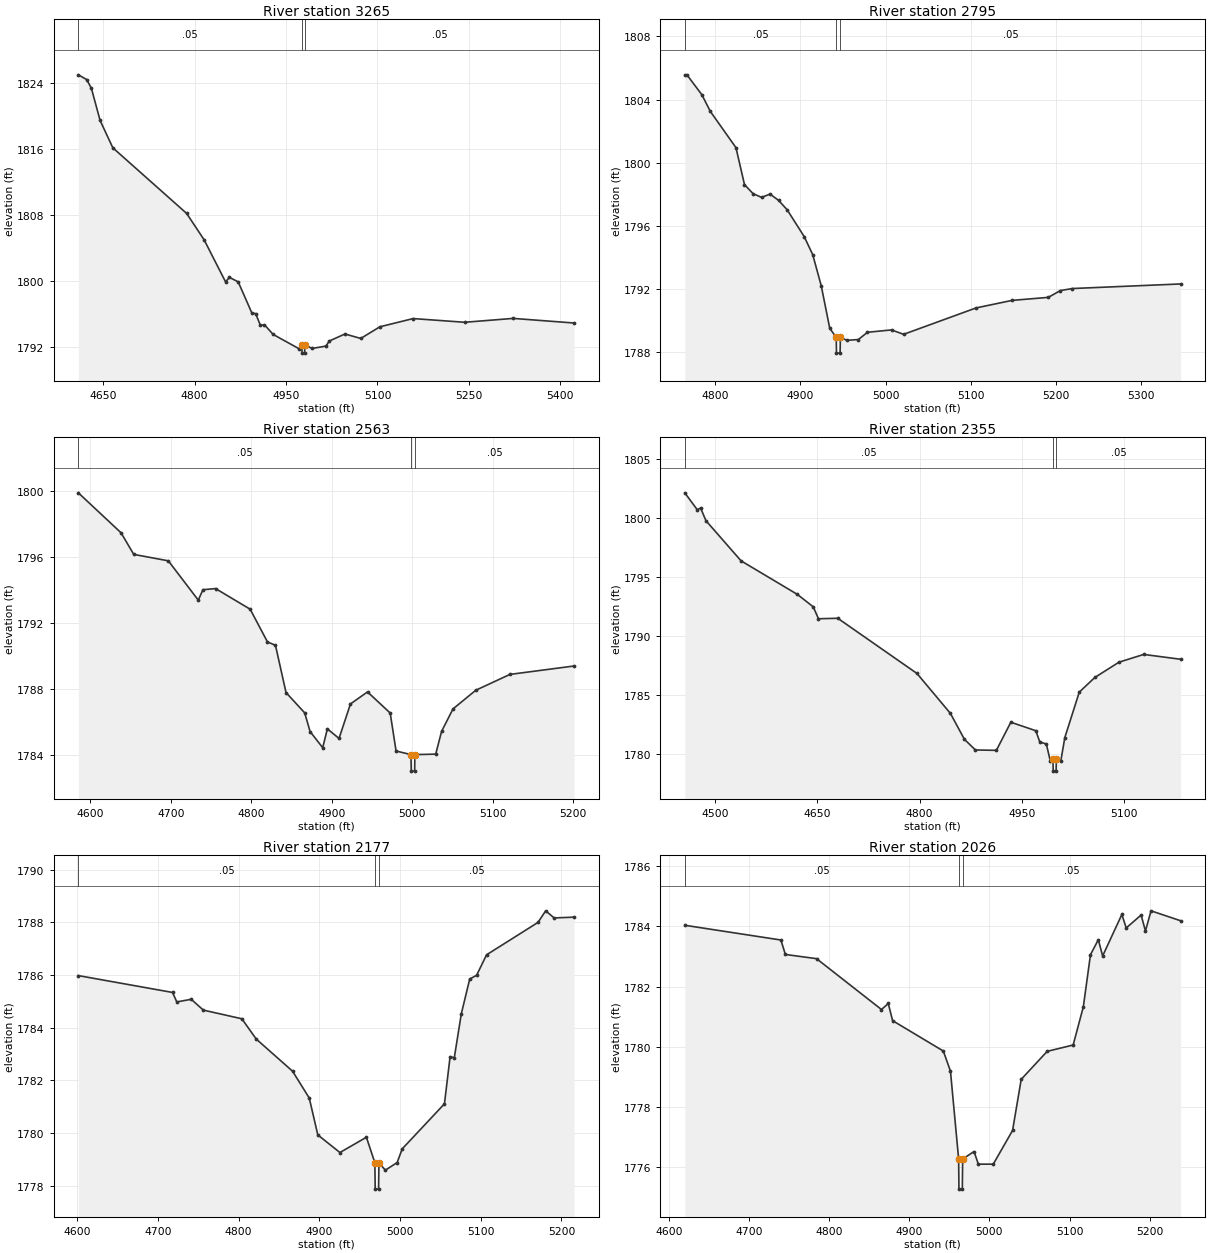
Type RM Length L Ch R = 1,3265,470,470,470
BEGIN DESCRIPTION:
Deadman 29 7.0
END DESCRIPTION:
XS GIS Cut Line= 3
      1660955.03      6921638.04      1661205.00      6921938.00
      1661342.58      6922337.72
#Sta/Elev= 30
  4609.4 1825.04  4623.0 1824.47  4630.8 1823.41  4645.1 1819.51  4666.0 1816.19
  4787.0 1808.24  4815.7 1805.04  4850.8 1799.95  4857.3 1800.48  4871.6 1799.94
  4893.8 1796.20  4900.3 1796.08  4908.1 1794.65  4914.6 1794.74  4928.9 1793.57
  4971.9 1791.81  4975.9 1792.30  4976.3 1791.30  4980.5 1791.30  4980.8 1792.30
  4992.7 1791.87  5015.5 1792.15  5021.0 1792.77  5046.7 1793.62  5072.6 1793.08
  5103.9 1794.49  5158.5 1795.49  5243.1 1795.04  5322.5 1795.51  5422.6 1794.95
#Mann=3,-1,0
  4609.4    0.05       0  4975.9    0.05       0  4980.8    0.05       0
Bank Sta=4975.9,4980.8
Exp/Cntr=0.3,0.1

Type RM Length L Ch R = 1,2795,232,232,232
BEGIN DESCRIPTION:
Deadman 29 6.0
END DESCRIPTION:
XS GIS Cut Line= 3
      1660805.00      6921937.97      1660805.00      6922138.00
      1661074.74      6922407.74
#Sta/Elev= 30
  4764.5 1805.57  4767.0 1805.57  4784.5 1804.31  4794.5 1803.25  4824.5 1800.96
  4834.5 1798.62  4844.5 1798.05  4854.5 1797.81  4864.5 1798.02  4874.5 1797.62
  4884.5 1797.03  4904.5 1795.33  4914.5 1794.19  4924.5 1792.22  4934.5 1789.52
  4942.1 1788.95  4942.4 1787.95  4946.6 1787.95  4947.0 1788.95  4954.5 1788.76
  4968.1 1788.81  4978.7 1789.27  5007.0 1789.42  5021.1 1789.14  5106.0 1790.81
  5148.4 1791.29  5190.8 1791.48  5204.9 1791.91  5219.1 1792.04  5346.0 1792.33
#Mann=3,-1,0
  4764.5    0.05       0  4942.1    0.03       0  4947.0    0.05       0
Bank Sta=4942.1,4947
Exp/Cntr=0.3,0.1

Type RM Length L Ch R = 1,2563,208,208,208
BEGIN DESCRIPTION:
Mapping XS 21674cca
END DESCRIPTION:
XS GIS Cut Line= 3
      1660474.55      6922014.86      1660634.26      6922289.13
      1660852.51      6922493.53
#Sta/Elev= 30
  4584.9 1799.89  4638.0 1797.47  4653.8 1796.16  4696.8 1795.77  4734.0 1793.39
  4739.8 1794.02  4755.5 1794.09  4798.5 1792.84  4820.0 1790.86  4830.0 1790.65
  4843.1 1787.79  4866.3 1786.56  4873.0 1785.43  4888.7 1784.45  4894.5 1785.59
  4909.0 1785.01  4923.2 1787.10  4944.4 1787.83  4972.6 1786.55  4979.9 1784.25
  4998.4 1784.03  4998.8 1783.03  5003.0 1783.03  5003.3 1784.03  5029.2 1784.06
  5036.5 1785.44  5050.7 1786.80  5079.0 1787.93  5121.5 1788.89  5201.3 1789.40
#Mann=3,-1,0
  4584.9    0.05       0  4998.4    0.03       0  5003.3    0.05       0
Bank Sta=4998.4,5003.3
Exp/Cntr=0.3,0.1

Type RM Length L Ch R = 1,2355,178,178,178
BEGIN DESCRIPTION:
Deadman 29 5.0
END DESCRIPTION:
XS GIS Cut Line= 3
      1660354.99      6922037.96      1660455.00      6922438.00
      1660721.68      6922604.22
#Sta/Elev= 30
  4455.9 1802.13  4474.0 1800.71  4479.1 1800.84  4486.9 1799.77  4538.4 1796.37
  4620.9 1793.53  4644.1 1792.48  4651.8 1791.47  4680.1 1791.51  4796.1 1786.84
  4845.1 1783.46  4865.7 1781.26  4881.8 1780.36  4912.5 1780.33  4933.7 1782.71
  4970.3 1781.99  4976.2 1781.03  4985.7 1780.87  4991.6 1779.41  4995.4 1779.57
  4995.8 1778.57  5000.0 1778.57  5000.4 1779.57  5006.9 1779.42  5012.8 1781.41
  5034.0 1785.26  5056.8 1786.50  5092.1 1787.79  5128.4 1788.45  5182.5 1788.04
#Mann=3,-1,0
  4455.9    0.05       0  4995.4    0.03       0  5000.4    0.05       0
Bank Sta=4995.4,5000.4
Exp/Cntr=0.3,0.1

Type RM Length L Ch R = 1,2177,151,151,151
BEGIN DESCRIPTION:
Mapping XS 8950ec19
END DESCRIPTION:
XS GIS Cut Line= 2
      1660031.17      6922478.07      1660618.74      6922657.33
#Sta/Elev= 30
  4601.5 1785.98  4718.2 1785.34  4723.5 1784.98  4741.4 1785.08  4756.3 1784.67
  4804.1 1784.34  4821.9 1783.57  4866.9 1782.35  4887.6 1781.33  4898.2 1779.93
  4925.6 1779.26  4958.4 1779.84  4968.9 1778.87  4969.3 1777.87  4973.5 1777.87
  4973.9 1778.87  4981.9 1778.59  4996.5 1778.88  5002.8 1779.40  5055.1 1781.11
  5062.1 1782.90  5067.3 1782.86  5076.0 1784.53  5086.4 1785.85  5094.9 1785.99
  5107.3 1786.77  5171.0 1788.00  5180.5 1788.44  5191.0 1788.17  5215.8 1788.20
#Mann=3,-1,0
  4601.5    0.05       0  4968.9    0.05       0  4973.9    0.05       0
Bank Sta=4968.9,4973.9
Exp/Cntr=0.3,0.1

Type RM Length L Ch R = 1,2026,136,136,136
BEGIN DESCRIPTION:
Mapping XS 015cd87a
END DESCRIPTION:
XS GIS Cut Line= 3
      1659954.78      6922527.86      1660177.20      6922640.73
      1660519.15      6922780.16
#Sta/Elev= 30
  4619.9 1784.04  4739.8 1783.55  4745.4 1783.07  4784.3 1782.93  4865.3 1781.24
  4873.8 1781.44  4879.2 1780.87  4942.5 1779.86  4951.4 1779.19  4961.6 1776.27
  4962.0 1775.27  4966.2 1775.27  4966.6 1776.27  4980.8 1776.52  4986.2 1776.10
  5004.8 1776.10  5028.9 1777.22  5039.7 1778.92  5072.1 1779.85  5104.5 1780.06
  5117.2 1781.33  5126.1 1783.06  5135.9 1783.56  5141.3 1783.02  5165.3 1784.40
  5170.7 1783.95  5189.3 1784.38  5194.7 1783.85  5201.7 1784.52  5238.6 1784.19
#Mann=3,-1,0
  4619.9    0.05       0  4961.6    0.03       0  4966.6    0.05       0
Bank Sta=4961.6,4966.6
Exp/Cntr=0.3,0.1

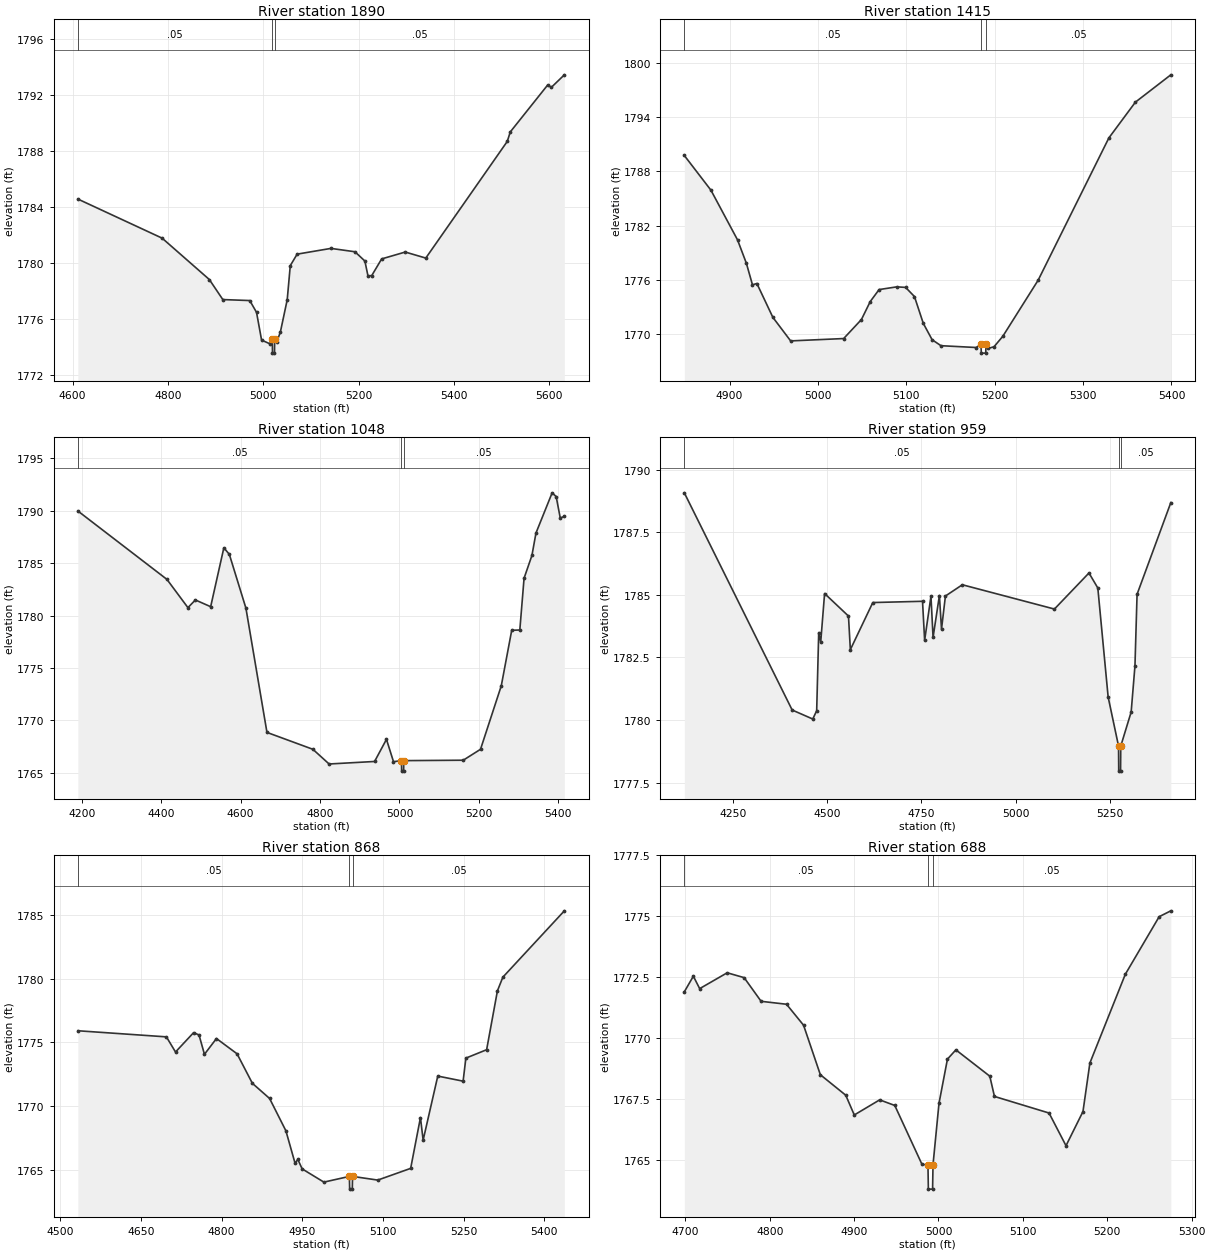
Type RM Length L Ch R = 1,1890,475,475,475
BEGIN DESCRIPTION:
Deadman 29 4.0
END DESCRIPTION:
XS GIS Cut Line= 3
      1659930.00      6922513.00      1660205.00      6922788.00
      1660694.24      6923187.60
#Sta/Elev= 30
  4611.2 1784.56  4788.0 1781.77  4887.0 1778.82  4915.3 1777.39  4971.8 1777.32
  4986.0 1776.48  4996.6 1774.50  5013.7 1774.24  5019.1 1774.57  5019.5 1773.57
  5023.7 1773.57  5024.1 1774.57  5028.1 1774.33  5036.0 1775.07  5050.4 1777.38
  5056.8 1779.81  5071.2 1780.63  5142.1 1781.04  5192.5 1780.80  5213.3 1780.14
  5219.8 1779.08  5227.7 1779.10  5248.5 1780.29  5298.0 1780.78  5341.1 1780.35
  5512.0 1788.67  5518.4 1789.35  5596.7 1792.69  5604.6 1792.53  5631.8 1793.42
#Mann=3,-1,0
  4611.2    0.05       0  5019.1    0.03       0  5024.1    0.05       0
Bank Sta=5019.1,5024.1
Exp/Cntr=0.3,0.1

Type RM Length L Ch R = 1,1415,367,367,367
BEGIN DESCRIPTION:
Deadman 29 3.0
END DESCRIPTION:
XS GIS Cut Line= 3
      1659805.00      6922637.96      1659814.57      6922788.86
      1659805.00      6923188.04
#Sta/Elev= 30
  4848.8 1789.74  4878.9 1785.91  4909.0 1780.42  4919.0 1777.84  4925.9 1775.46
  4930.9 1775.60  4949.0 1771.86  4969.1 1769.26  5029.1 1769.52  5049.2 1771.62
  5059.2 1773.61  5069.2 1774.93  5089.2 1775.23  5099.2 1775.17  5109.2 1774.16
  5119.2 1771.20  5129.2 1769.39  5139.2 1768.73  5179.2 1768.53  5184.4 1768.91
  5184.9 1767.91  5189.8 1767.91  5190.3 1768.91  5192.4 1768.43  5199.2 1768.61
  5209.2 1769.77  5249.2 1775.97  5329.2 1791.68  5359.2 1795.63  5399.3 1798.65
#Mann=3,-1,0
  4848.8    0.05       0  5184.4    0.03       0  5190.3    0.05       0
Bank Sta=5184.4,5190.3
Exp/Cntr=0.3,0.1

Type RM Length L Ch R = 1,1048,89,89,89
BEGIN DESCRIPTION:
Mapping XS b180adfb
END DESCRIPTION:
XS GIS Cut Line= 6
      1659845.21      6922272.25      1659709.11      6922730.36
      1659569.67      6922730.36      1659466.76      6922756.92
      1659453.48      6922793.44      1659539.79      6923248.24
#Sta/Elev= 30
  4189.9 1789.96  4414.3 1783.44  4467.1 1780.75  4485.9 1781.48  4524.4 1780.84
  4557.6 1786.45  4571.4 1785.83  4613.2 1780.70  4666.2 1768.86  4781.9 1767.25
  4822.7 1765.85  4937.3 1766.09  4967.2 1768.20  4984.9 1766.07  5005.0 1766.17
  5005.5 1765.17  5010.4 1765.17  5010.9 1766.17  5160.6 1766.21  5204.1 1767.25
  5256.4 1773.30  5282.7 1778.59  5303.1 1778.62  5313.8 1783.55  5333.6 1785.72
  5343.8 1787.86  5384.5 1791.69  5394.7 1791.33  5404.9 1789.30  5415.3 1789.44
#Mann=3,-1,0
  4189.9    0.05       0  5005.0    0.03       0  5010.9    0.05       0
Bank Sta=5005,5010.9
Exp/Cntr=0.3,0.1

Type RM Length L Ch R = 1,959,91,91,91
BEGIN DESCRIPTION:
Mapping XS edfc368c
END DESCRIPTION:
XS GIS Cut Line= 6
      1659795.42      6922272.24      1659682.55      6922637.41
      1659490.00      6922657.33      1659377.12      6922713.77
      1659363.84      6922753.60      1659466.77      6923291.47
#Sta/Elev= 30
  4120.6 1789.07  4406.9 1780.40  4461.6 1780.04  4472.0 1780.37  4477.4 1783.49
  4482.7 1783.11  4493.0 1785.05  4556.4 1784.15  4561.4 1782.81  4621.0 1784.69
  4753.0 1784.74  4758.6 1783.18  4775.4 1784.94  4781.0 1783.30  4797.8 1784.97
  4803.4 1783.63  4813.8 1784.95  4858.7 1785.40  5103.2 1784.43  5194.9 1785.87
  5218.4 1785.27  5245.8 1780.92  5273.4 1778.96  5273.9 1777.96  5278.8 1777.96
  5279.3 1778.96  5306.9 1780.32  5317.0 1782.16  5322.6 1785.02  5412.2 1788.68
#Mann=3,-1,0
  4120.6    0.05       0  5273.4    0.03       0  5279.3    0.05       0
Bank Sta=5273.4,5279.3
Exp/Cntr=0.3,0.1

Type RM Length L Ch R = 1,868,180,180,180
BEGIN DESCRIPTION:
Mapping XS 3932e6ad
END DESCRIPTION:
XS GIS Cut Line= 3
      1659234.38      6922424.99      1659277.53      6922730.36
      1659353.89      6923321.34
#Sta/Elev= 30
  4532.9 1775.91  4697.5 1775.43  4714.4 1774.24  4748.0 1775.76  4758.1 1775.58
  4768.2 1774.06  4790.5 1775.30  4828.8 1774.10  4857.3 1771.78  4889.3 1770.59
  4919.6 1768.05  4936.7 1765.49  4941.7 1765.81  4949.8 1765.06  4990.2 1764.02
  5037.6 1764.47  5038.1 1763.47  5043.0 1763.47  5043.5 1764.47  5090.3 1764.18
  5151.5 1765.10  5169.7 1769.09  5174.7 1767.32  5201.9 1772.35  5249.0 1771.95
  5254.1 1773.76  5292.7 1774.42  5312.8 1779.05  5322.9 1780.12  5437.2 1785.33
#Mann=3,-1,0
  4532.9    0.05       0  5037.6    0.05       0  5043.5    0.05       0
Bank Sta=5037.6,5043.5
Exp/Cntr=0.3,0.1

Type RM Length L Ch R = 1,688,349,349,349
BEGIN DESCRIPTION:
Mapping XS 438530e1
END DESCRIPTION:
XS GIS Cut Line= 2
      1659108.21      6922637.37      1659158.01      6923211.71
#Sta/Elev= 30
  4698.8 1771.91  4709.5 1772.55  4717.0 1772.04  4749.6 1772.69  4769.7 1772.49
  4789.8 1771.52  4819.9 1771.40  4840.1 1770.54  4860.0 1768.51  4890.1 1767.67
  4900.2 1766.86  4930.3 1767.48  4948.2 1767.25  4980.5 1764.83  4987.5 1764.82
  4988.0 1763.82  4993.0 1763.82  4993.5 1764.82  5000.6 1767.34  5010.6 1769.15
  5020.6 1769.53  5060.8 1768.45  5066.3 1767.62  5131.0 1766.94  5151.1 1765.60
  5171.2 1767.00  5179.4 1768.99  5221.4 1772.63  5261.5 1774.99  5275.3 1775.23
#Mann=3,-1,0
  4698.8    0.05       0  4987.5    0.05       0  4993.5    0.05       0
Bank Sta=4987.5,4993.5
Exp/Cntr=0.3,0.1

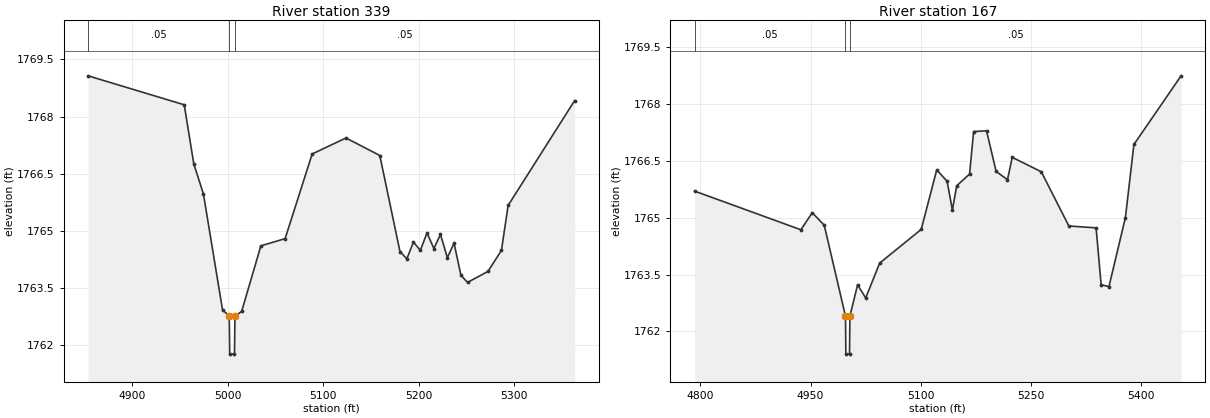
Type RM Length L Ch R = 1,339,172,172,172
BEGIN DESCRIPTION:
Mapping XS 7c9b8f6e
END DESCRIPTION:
XS GIS Cut Line= 3
      1658805.26      6922767.57      1658817.76      6922969.14
      1659031.15      6923190.20
#Sta/Elev= 30
  4853.8 1769.07  4954.4 1768.31  4964.4 1766.76  4974.5 1765.97  4994.5 1762.93
  5001.5 1762.77  5002.0 1761.77  5007.0 1761.77  5007.5 1762.77  5014.5 1762.89
  5034.6 1764.61  5060.0 1764.80  5088.3 1767.02  5123.7 1767.44  5159.1 1766.98
  5180.2 1764.46  5187.4 1764.27  5194.3 1764.71  5201.5 1764.49  5208.5 1764.95
  5215.7 1764.54  5222.6 1764.91  5229.8 1764.30  5236.8 1764.68  5244.0 1763.84
  5250.9 1763.65  5272.3 1763.94  5286.4 1764.49  5293.4 1765.67  5363.0 1768.42
#Mann=3,-1,0
  4853.8    0.05       0  5001.5    0.03       0  5007.5    0.05       0
Bank Sta=5001.5,5007.5
Exp/Cntr=0.3,0.1

Type RM Length L Ch R = 1,167,0,0,0
BEGIN DESCRIPTION:
Deadman 29 1.0
END DESCRIPTION:
XS GIS Cut Line= 4
      1658586.52      6922781.65      1658663.08      6922997.27
      1658752.39      6923082.95      1659033.98      6923211.71
#Sta/Elev= 30
  4792.2 1765.70  4936.9 1764.68  4952.4 1765.13  4968.7 1764.80  4997.6 1762.40
  4998.1 1761.40  5003.1 1761.40  5003.6 1762.40  5014.1 1763.23  5025.1 1762.88
  5044.1 1763.80  5100.7 1764.69  5121.8 1766.26  5135.9 1765.96  5143.1 1765.20
  5149.0 1765.84  5166.5 1766.15  5172.0 1767.27  5189.6 1767.29  5202.6 1766.22
  5218.1 1766.00  5224.6 1766.59  5264.1 1766.21  5301.6 1764.78  5338.7 1764.73
  5345.6 1763.23  5356.2 1763.18  5378.6 1765.00  5390.2 1766.93  5454.4 1768.74
#Mann=3,-1,0
  4792.2    0.05       0  4997.6    0.03       0  5003.6    0.05       0
Bank Sta=4997.6,5003.6
Exp/Cntr=0.3,0.1

Chan Stop Cuts=-1