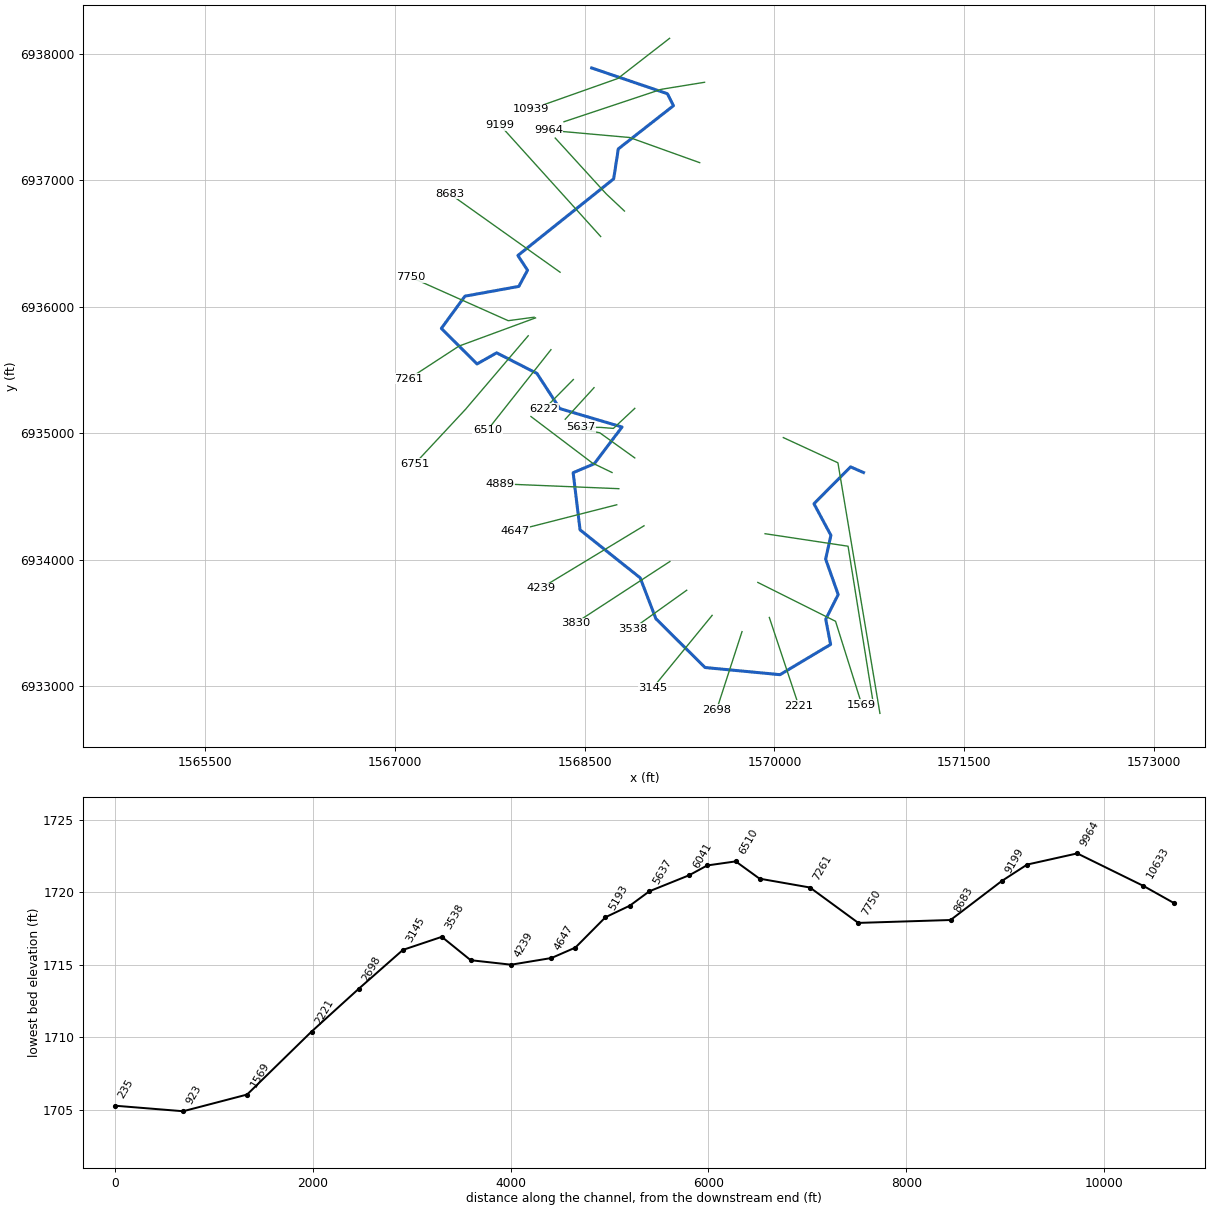
--- Deadman 30.prj (project) ---

Proj Title=Deadman 30 Base Level Engineering
Current Plan=p01
Default Exp/Contr=0.3,0.1
English Units
Geom File=g01
Flow File=f01
Plan File=p01
BEGIN DESCRIPTION:
Deadman 30
END DESCRIPTION:

--- Deadman 30.p01 (plan) ---

Plan Title=Multiple Run
Short Identifier=Multiple
Geom File=g01
Flow File=f01
Subcritical Flow
K Sum by GR= 0
Std Step Tol= 0.01
Critical Tol= 0.01
Num of Std Step Trials= 20
Max Error Tol= 0.3
Flow Tol Ratio= 0.001
Split Flow NTrial= 30
Split Flow Tol= 0.02
Split Flow Ratio= 0.02
Log Output Level= 0
Friction Slope Method= 1
Unsteady Friction Slope Method= 2
Unsteady Bridges Friction Slope Method= 1
Parabolic Critical Depth
Global Vel Dist=  1 , 1 , 1
Global Log Level= 0
CheckData=True
Encroach Param= -1, 0, 0, 0
BEGIN DESCRIPTION:
Multiple Run
END DESCRIPTION:

--- Deadman 30.f01 (steady flow) ---

Flow Title=Multiple
Number of Profiles=7
Profile Names=10-year,25-year,50-year,1pct_min,100-year,1pct_plu,500-year
River Rch & RM= Deadman 30,Reach-1,10939
     171     224     265     155     310     618     430
Boundary for River Rch & Prof#=Deadman 30,Reach-1,1
Up Type=0
Dn Type=3
Dn Slope=0.005
Boundary for River Rch & Prof#=Deadman 30,Reach-1,2
Up Type=0
Dn Type=3
Dn Slope=0.005
Boundary for River Rch & Prof#=Deadman 30,Reach-1,3
Up Type=0
Dn Type=3
Dn Slope=0.005
Boundary for River Rch & Prof#=Deadman 30,Reach-1,4
Up Type=0
Dn Type=3
Dn Slope=0.005
Boundary for River Rch & Prof#=Deadman 30,Reach-1,5
Up Type=0
Dn Type=3
Dn Slope=0.005
Boundary for River Rch & Prof#=Deadman 30,Reach-1,6
Up Type=0
Dn Type=3
Dn Slope=0.005
Boundary for River Rch & Prof#=Deadman 30,Reach-1,7
Up Type=0
Dn Type=3
Dn Slope=0.005

--- Deadman 30.g01 (geometry) ---

Geom Title=Existing Conditions

River Reach=Deadman 30,Reach-1
Reach XY= 30
      1568555.00      6937888.00      1569153.78      6937684.48
      1569201.92      6937589.67      1568765.48      6937247.80
      1568728.97      6937010.81      1567971.20      6936404.67
      1568047.69      6936288.09      1567978.71      6936160.36
      1567552.46      6936082.99      1567365.95      6935828.00
      1567648.05      6935546.85      1567803.35      6935634.89
      1568122.13      6935471.70      1568302.69      6935193.82
      1568794.98      6935048.05      1568575.54      6934757.47
      1568408.43      6934686.78      1568463.04      6934234.68
      1568938.55      6933855.13      1569062.86      6933531.83
      1569451.58      6933145.79      1570044.50      6933089.20
      1570444.82      6933328.29      1570406.09      6933527.46
      1570504.91      6933722.60      1570405.51      6934003.22
      1570447.19      6934191.41      1570313.04      6934441.32
      1570602.66      6934732.94      1570705.00      6934688.00

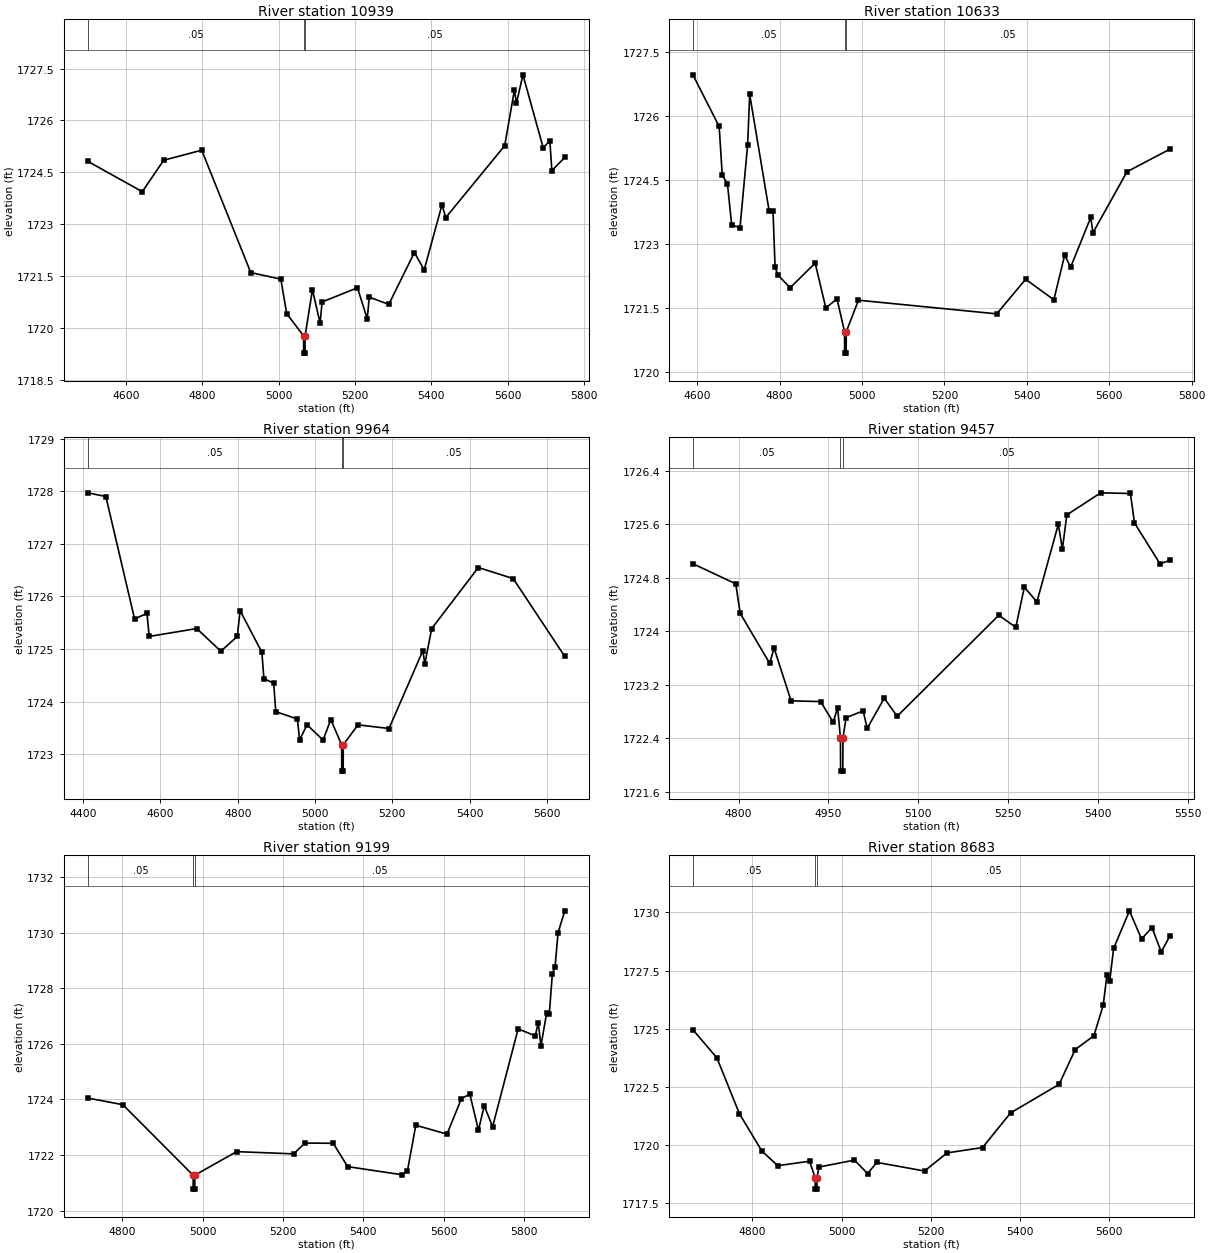
Type RM Length L Ch R = 1,10939,306,306,306
BEGIN DESCRIPTION:
Deadman 30 7.0
END DESCRIPTION:
XS GIS Cut Line= 3
      1569171.14      6938122.37      1568761.90      6937804.76
      1568071.69      6937560.44
#Sta/Elev= 30
  4499.4 1724.82  4642.6 1723.94  4698.7 1724.85  4798.3 1725.14  4926.8 1721.60
  5005.6 1721.41  5021.1 1720.41  5065.1 1719.77  5065.4 1719.27  5069.0 1719.27
  5069.2 1719.77  5088.4 1721.10  5108.5 1720.14  5113.8 1720.75  5206.4 1721.16
  5232.0 1720.26  5237.3 1720.89  5288.5 1720.68  5355.6 1722.18  5381.2 1721.68
  5427.9 1723.56  5437.7 1723.19  5592.2 1725.27  5617.8 1726.89  5623.1 1726.50
  5640.0 1727.32  5693.1 1725.21  5710.5 1725.41  5715.8 1724.55  5749.6 1724.93
#Mann=3,-1,0
  4499.4    0.05       0  5065.1    0.04       0  5069.2    0.05       0
Bank Sta=5065.1,5069.2
Exp/Cntr=0.3,0.1

Type RM Length L Ch R = 1,10633,669,669,669
BEGIN DESCRIPTION:
Mapping XS d9b559b4
END DESCRIPTION:
XS GIS Cut Line= 3
      1569447.84      6937774.81      1569105.41      6937719.17
      1568335.95      6937462.68
#Sta/Elev= 30
  4589.5 1726.96  4653.2 1725.75  4660.7 1724.61  4673.4 1724.40  4683.6 1723.44
  4703.8 1723.38  4722.3 1725.32  4727.3 1726.50  4774.7 1723.76  4783.8 1723.78
  4788.9 1722.46  4795.0 1722.28  4825.4 1721.97  4886.2 1722.55  4912.0 1721.50
  4939.3 1721.71  4957.5 1720.94  4957.8 1720.44  4961.4 1720.44  4961.7 1720.94
  4991.2 1721.68  5326.9 1721.36  5397.0 1722.17  5465.5 1721.69  5491.9 1722.74
  5506.1 1722.45  5555.1 1723.62  5560.4 1723.26  5643.1 1724.69  5747.5 1725.22
#Mann=3,-1,0
  4589.5    0.05       0  4957.5    0.03       0  4961.7    0.05       0
Bank Sta=4957.5,4961.7
Exp/Cntr=0.3,0.1

Type RM Length L Ch R = 1,9964,507,507,507
BEGIN DESCRIPTION:
Deadman 30 6.0
END DESCRIPTION:
XS GIS Cut Line= 3
      1569409.35      6937138.99      1568855.00      6937338.00
      1568212.15      6937395.52
#Sta/Elev= 30
  4411.7 1727.97  4458.8 1727.90  4533.2 1725.57  4565.1 1725.68  4571.0 1725.24
  4693.9 1725.39  4756.3 1724.96  4798.8 1725.24  4806.2 1725.73  4862.4 1724.94
  4867.7 1724.44  4893.1 1724.35  4898.4 1723.81  4954.6 1723.67  4959.9 1723.27
  4979.4 1723.56  5020.8 1723.27  5040.8 1723.66  5068.9 1723.18  5069.1 1722.68
  5072.8 1722.68  5073.1 1723.18  5111.1 1723.56  5191.4 1723.49  5279.0 1724.97
  5284.0 1724.72  5301.9 1725.39  5422.4 1726.55  5512.7 1726.34  5646.1 1724.86
#Mann=3,-1,0
  4411.7    0.05       0  5068.9    0.04       0  5073.1    0.05       0
Bank Sta=5068.9,5073.1
Exp/Cntr=0.3,0.1

Type RM Length L Ch R = 1,9457,258,258,258
BEGIN DESCRIPTION:
Mapping XS 18ad58a4
END DESCRIPTION:
XS GIS Cut Line= 3
      1568814.37      6936756.18      1568668.85      6936893.13
      1568266.98      6937333.49
#Sta/Elev= 30
  4723.9 1725.01  4795.4 1724.71  4802.7 1724.27  4852.0 1723.52  4859.3 1723.75
  4887.7 1722.96  4937.0 1722.95  4957.9 1722.64  4965.3 1722.86  4970.0 1722.41
  4970.3 1721.91  4974.0 1721.91  4974.2 1722.41  4979.5 1722.71  5007.9 1722.81
  5014.7 1722.55  5043.1 1723.00  5064.7 1722.73  5234.2 1724.24  5262.6 1724.06
  5276.8 1724.66  5297.8 1724.44  5333.5 1725.60  5340.3 1725.23  5347.7 1725.74
  5404.2 1726.07  5453.8 1726.06  5460.6 1725.62  5503.1 1725.01  5519.9 1725.06
#Mann=3,-1,0
  4723.9    0.05       0  4970.0    0.04       0  4974.2    0.05       0
Bank Sta=4970,4974.2
Exp/Cntr=0.3,0.1

Type RM Length L Ch R = 1,9199,516,516,516
BEGIN DESCRIPTION:
Mapping XS 55e6ed27
END DESCRIPTION:
XS GIS Cut Line= 2
      1568626.05      6936555.02      1567829.97      6937436.70
#Sta/Elev= 30
  4713.9 1724.05  4801.5 1723.81  4976.5 1721.27  4976.8 1720.77  4980.5 1720.77
  4980.7 1721.27  5084.7 1722.12  5226.7 1722.04  5255.1 1722.43  5325.4 1722.42
  5361.2 1721.58  5495.7 1721.29  5509.9 1721.41  5530.9 1723.07  5608.6 1722.75
  5644.5 1724.03  5665.4 1724.19  5687.0 1722.89  5701.2 1723.77  5722.2 1723.02
  5785.7 1726.54  5828.3 1726.29  5835.8 1726.76  5842.5 1725.93  5856.7 1727.11
  5863.4 1727.09  5870.9 1728.52  5877.6 1728.77  5885.1 1730.00  5901.8 1730.79
#Mann=3,-1,0
  4713.9    0.05       0  4976.5    0.04       0  4980.7    0.05       0
Bank Sta=4976.5,4980.7
Exp/Cntr=0.3,0.1

Type RM Length L Ch R = 1,8683,933,933,933
BEGIN DESCRIPTION:
Mapping XS 0e818cda
END DESCRIPTION:
XS GIS Cut Line= 2
      1568305.04      6936272.55      1567432.01      6936893.08
#Sta/Elev= 30
  4666.4 1724.95  4720.3 1723.74  4770.7 1721.34  4821.2 1719.73  4856.8 1719.10
  4928.2 1719.29  4940.8 1718.59  4941.1 1718.09  4944.8 1718.09  4945.1 1718.59
  4949.1 1719.04  5029.0 1719.34  5058.5 1718.76  5079.4 1719.24  5186.4 1718.87
  5236.9 1719.65  5316.7 1719.88  5379.5 1721.37  5488.5 1722.60  5524.7 1724.10
  5566.5 1724.69  5587.4 1726.00  5596.0 1727.32  5602.1 1727.04  5610.8 1728.45
  5646.4 1730.07  5673.5 1728.86  5696.9 1729.35  5717.8 1728.30  5737.5 1729.00
#Mann=3,-1,0
  4666.4    0.05       0  4940.8    0.04       0  4945.1    0.05       0
Bank Sta=4940.8,4945.1
Exp/Cntr=0.3,0.1

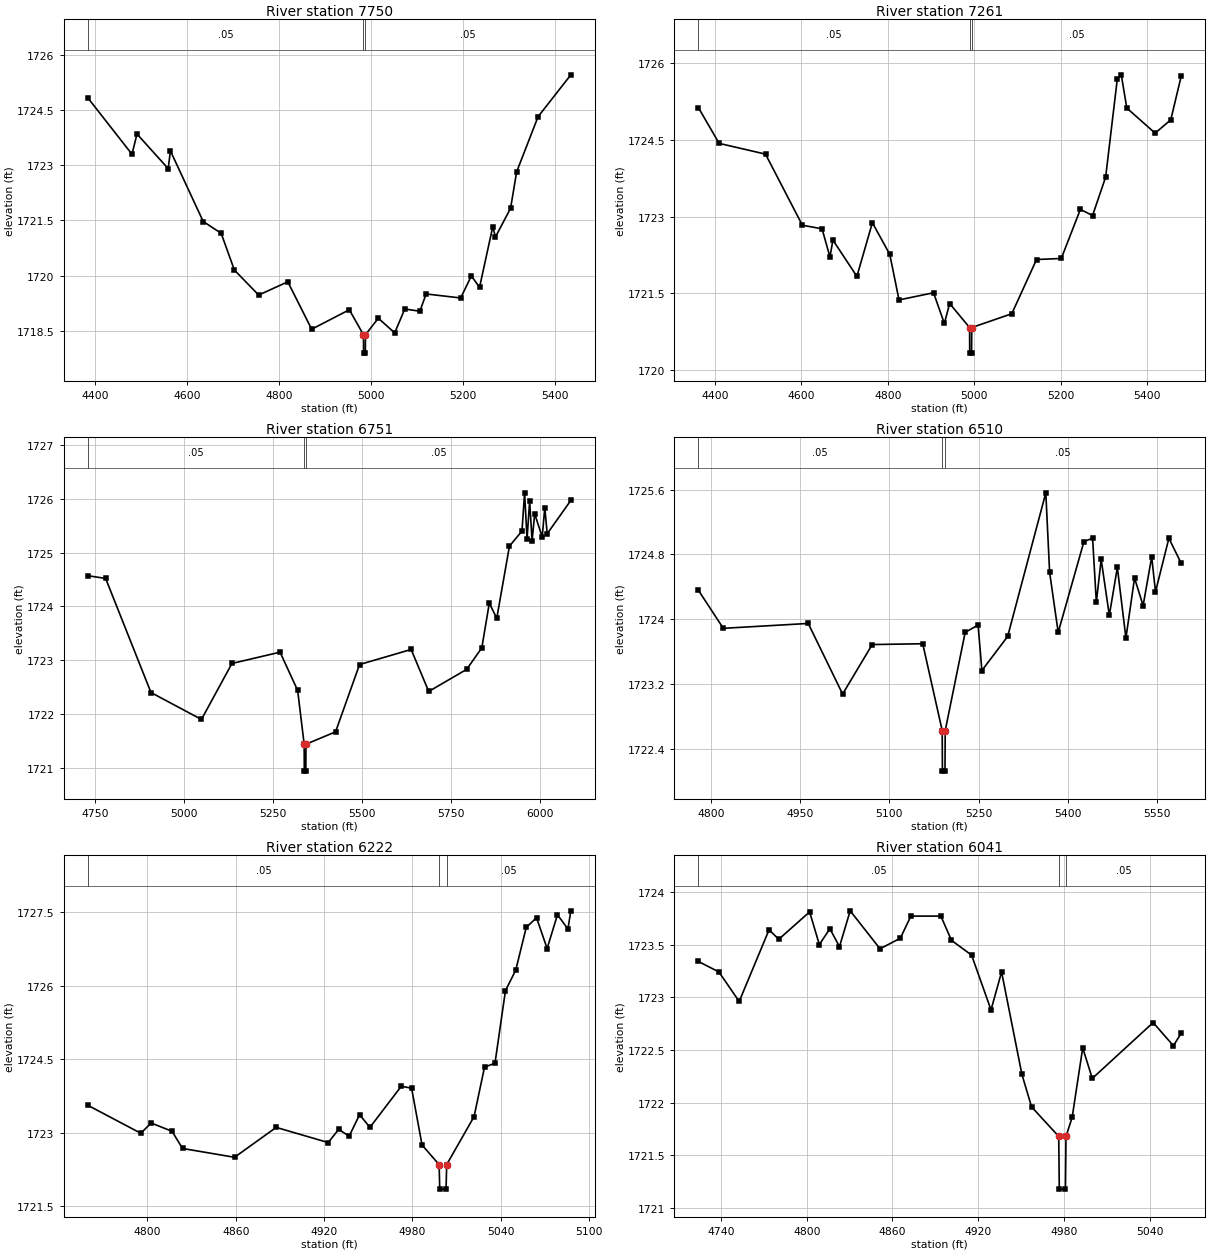
Type RM Length L Ch R = 1,7750,489,489,489
BEGIN DESCRIPTION:
Mapping XS 57822adc
END DESCRIPTION:
XS GIS Cut Line= 3
      1568099.85      6935916.72      1567894.97      6935889.03
      1567125.39      6936232.30
#Sta/Elev= 30
  4385.3 1724.83  4481.0 1723.30  4491.9 1723.85  4559.6 1722.91  4564.6 1723.39
  4635.8 1721.47  4674.8 1721.15  4703.5 1720.15  4756.3 1719.47  4819.6 1719.83
  4871.5 1718.54  4953.3 1719.07  4984.0 1718.39  4984.3 1717.89  4988.1 1717.89
  4988.4 1718.39  5016.3 1718.84  5051.9 1718.44  5073.8 1719.09  5106.6 1719.03
  5120.2 1719.50  5195.3 1719.39  5218.5 1719.99  5236.3 1719.68  5265.0 1721.33
  5270.9 1721.05  5303.7 1721.83  5316.9 1722.82  5363.4 1724.32  5434.7 1725.46
#Mann=3,-1,0
  4385.3    0.05       0  4984.0    0.04       0  4988.4    0.05       0
Bank Sta=4984,4988.4
Exp/Cntr=0.3,0.1

Type RM Length L Ch R = 1,7261,510,510,510
BEGIN DESCRIPTION:
Deadman 30 5.0
END DESCRIPTION:
XS GIS Cut Line= 3
      1568110.92      6935911.19      1567505.00      6935688.00
      1567109.37      6935429.88
#Sta/Elev= 30
  4361.4 1725.13  4409.5 1724.43  4516.9 1724.22  4602.2 1722.83  4647.8 1722.76
  4666.1 1722.21  4672.9 1722.54  4728.5 1721.83  4764.3 1722.88  4804.6 1722.26
  4826.0 1721.37  4905.9 1721.51  4931.0 1720.91  4943.2 1721.30  4989.4 1720.83
  4989.7 1720.33  4994.0 1720.33  4994.4 1720.83  5087.1 1721.10  5144.4 1722.16
  5201.7 1722.18  5245.9 1723.14  5274.1 1723.02  5304.4 1723.77  5331.4 1725.69
  5340.6 1725.77  5353.4 1725.12  5419.0 1724.63  5455.2 1724.89  5479.5 1725.75
#Mann=3,-1,0
  4361.4    0.05       0  4989.4    0.03       0  4994.4    0.05       0
Bank Sta=4989.4,4994.4
Exp/Cntr=0.3,0.1

Type RM Length L Ch R = 1,6751,241,241,241
BEGIN DESCRIPTION:
Mapping XS b0151a29
END DESCRIPTION:
XS GIS Cut Line= 3
      1568053.06      6935769.81      1567556.57      6935187.44
      1567153.97      6934755.31
#Sta/Elev= 30
  4730.3 1724.57  4780.0 1724.52  4907.3 1722.40  5049.0 1721.90  5134.6 1722.94
  5269.7 1723.15  5319.1 1722.44  5337.4 1721.44  5337.8 1720.94  5342.1 1720.94
  5342.5 1721.44  5425.6 1721.67  5492.9 1722.92  5637.8 1723.20  5687.1 1722.42
  5793.6 1722.83  5836.2 1723.23  5857.2 1724.06  5878.2 1723.78  5913.8 1725.12
  5949.0 1725.40  5956.3 1726.11  5963.2 1725.25  5970.5 1725.96  5977.3 1725.22
  5984.7 1725.72  6005.7 1725.29  6013.0 1725.83  6019.8 1725.35  6086.2 1725.97
#Mann=3,-1,0
  4730.3    0.05       0  5337.4    0.04       0  5342.5    0.05       0
Bank Sta=5337.4,5342.5
Exp/Cntr=0.3,0.1

Type RM Length L Ch R = 1,6510,288,288,288
BEGIN DESCRIPTION:
Mapping XS 2ebefc5b
END DESCRIPTION:
XS GIS Cut Line= 2
      1568232.91      6935659.81      1567729.96      6935023.09
#Sta/Elev= 30
  4779.1 1724.36  4821.0 1723.89  4963.7 1723.95  5021.5 1723.08  5071.2 1723.69
  5156.1 1723.70  5188.8 1722.63  5189.2 1722.13  5193.5 1722.13  5193.9 1722.63
  5227.4 1723.84  5249.1 1723.93  5255.5 1723.37  5298.8 1723.79  5362.9 1725.56
  5369.3 1724.58  5383.7 1723.84  5427.0 1724.96  5441.5 1725.00  5447.8 1724.21
  5455.9 1724.74  5469.6 1724.05  5483.1 1724.64  5497.5 1723.77  5512.0 1724.51
  5526.4 1724.17  5540.8 1724.77  5547.2 1724.34  5569.7 1725.00  5590.5 1724.69
#Mann=3,-1,0
  4779.1    0.05       0  5188.8    0.04       0  5193.9    0.05       0
Bank Sta=5188.8,5193.9
Exp/Cntr=0.3,0.1

Type RM Length L Ch R = 1,6222,181,181,181
BEGIN DESCRIPTION:
Mapping XS 6b72d69f
END DESCRIPTION:
XS GIS Cut Line= 2
      1568410.08      6935423.66      1568179.63      6935190.53
#Sta/Elev= 30
  4759.7 1723.56  4795.6 1722.99  4802.6 1723.20  4816.8 1723.03  4823.9 1722.68
  4859.2 1722.50  4887.5 1723.11  4922.8 1722.80  4929.9 1723.07  4937.0 1722.93
  4944.1 1723.37  4951.1 1723.11  4972.4 1723.95  4979.4 1723.91  4986.5 1722.75
  4998.1 1722.35  4998.5 1721.85  5002.8 1721.85  5003.2 1722.35  5021.8 1723.33
  5028.9 1724.34  5036.0 1724.42  5043.1 1725.90  5050.1 1726.32  5057.2 1727.19
  5064.2 1727.39  5071.4 1726.76  5078.4 1727.45  5085.5 1727.16  5087.5 1727.53
#Mann=3,-1,0
  4759.7    0.05       0  4998.1    0.04       0  5003.2    0.05       0
Bank Sta=4998.1,5003.2
Exp/Cntr=0.3,0.1

Type RM Length L Ch R = 1,6041,404,404,404
BEGIN DESCRIPTION:
Mapping XS 7380869c
END DESCRIPTION:
XS GIS Cut Line= 2
      1568573.74      6935359.19      1568345.64      6935109.62
#Sta/Elev= 30
  4724.1 1723.34  4738.5 1723.24  4752.7 1722.96  4773.6 1723.64  4780.4 1723.55
  4802.0 1723.81  4808.8 1723.50  4816.2 1723.65  4822.9 1723.48  4830.4 1723.82
  4851.3 1723.46  4865.5 1723.56  4872.9 1723.77  4893.9 1723.77  4901.3 1723.54
  4915.4 1723.40  4929.0 1722.88  4936.4 1723.24  4950.6 1722.27  4957.4 1721.96
  4976.4 1721.68  4976.8 1721.18  4981.1 1721.18  4981.5 1721.68  4985.8 1721.86
  4993.2 1722.52  4999.9 1722.23  5042.5 1722.76  5056.7 1722.54  5062.2 1722.66
#Mann=3,-1,0
  4724.1    0.05       0  4976.4    0.04       0  4981.5    0.05       0
Bank Sta=4976.4,4981.5
Exp/Cntr=0.3,0.1

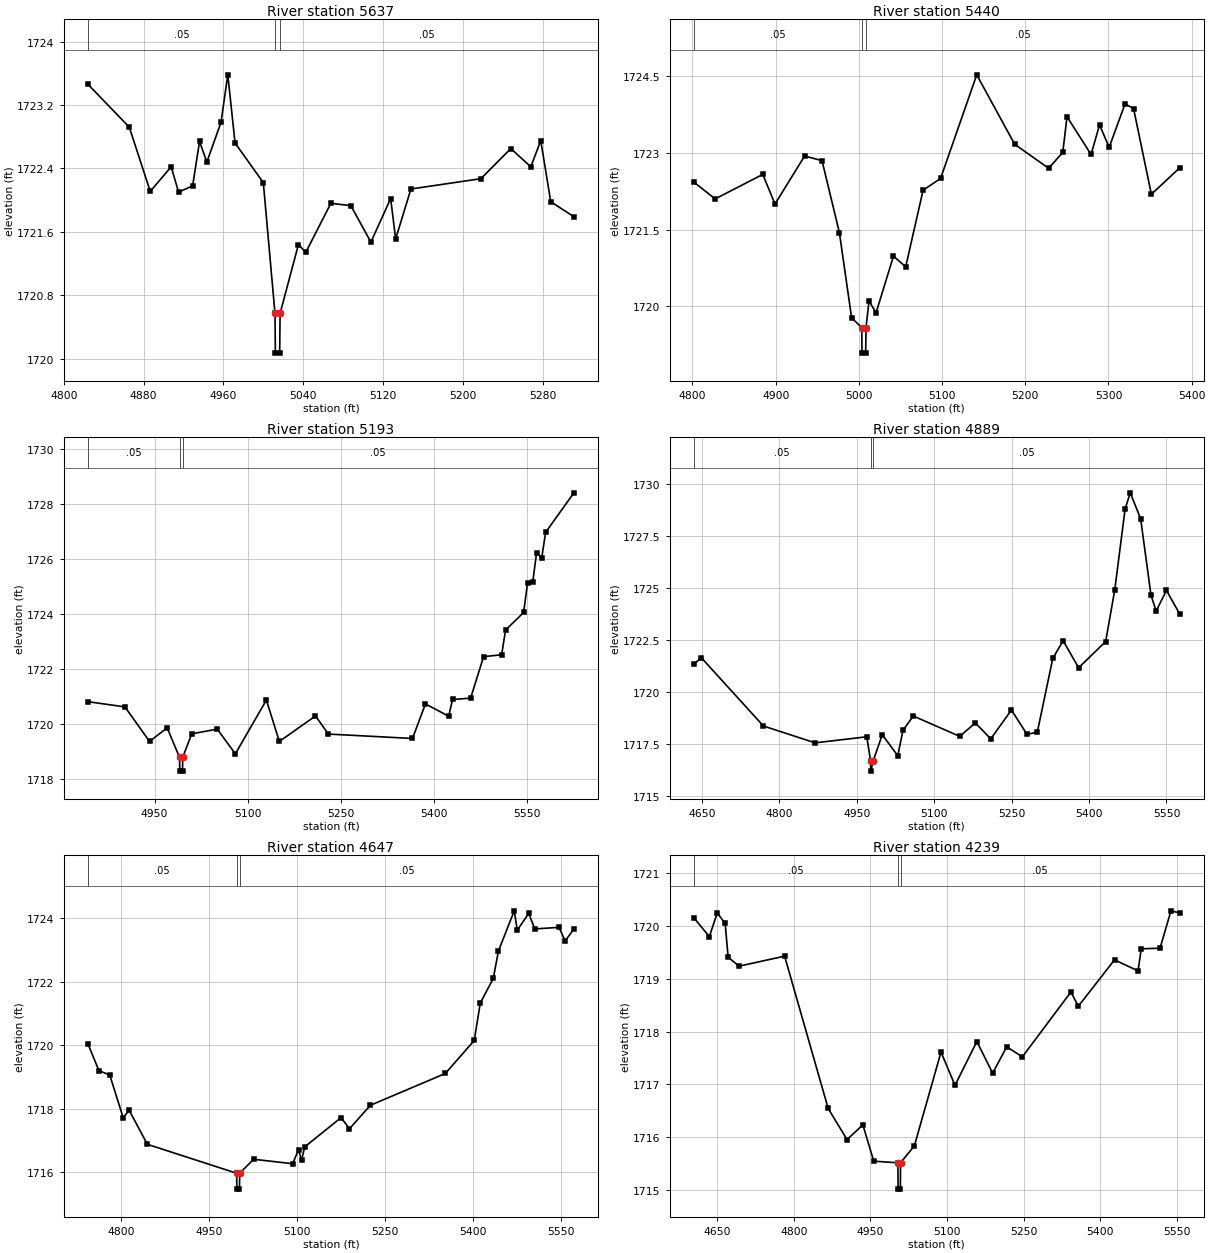
Type RM Length L Ch R = 1,5637,197,197,197
BEGIN DESCRIPTION:
Mapping XS 6dc1c83c
END DESCRIPTION:
XS GIS Cut Line= 4
      1568895.79      6935195.46      1568726.74      6935037.14
      1568622.07      6935045.19      1568471.76      6935045.19
#Sta/Elev= 30
  4824.3 1723.46  4865.7 1722.92  4886.7 1722.11  4907.7 1722.42  4915.1 1722.10
  4929.2 1722.18  4936.1 1722.74  4943.4 1722.48  4957.6 1722.98  4964.4 1723.58
  4971.7 1722.72  5000.0 1722.22  5011.7 1720.57  5012.1 1720.07  5016.4 1720.07
  5016.8 1720.57  5035.2 1721.44  5042.5 1721.34  5067.7 1721.96  5087.7 1721.93
  5107.8 1721.47  5127.6 1722.02  5132.6 1721.51  5147.9 1722.14  5218.0 1722.27
  5248.0 1722.65  5268.0 1722.42  5278.0 1722.75  5288.0 1721.98  5311.2 1721.79
#Mann=3,-1,0
  4824.3    0.05       0  5011.7    0.04       0  5016.8    0.05       0
Bank Sta=5011.7,5016.8
Exp/Cntr=0.3,0.1

Type RM Length L Ch R = 1,5440,247,247,247
BEGIN DESCRIPTION:
Mapping XS 680bc98c
END DESCRIPTION:
XS GIS Cut Line= 3
      1568895.86      6934803.62      1568619.39      6935002.25
      1568380.55      6935050.56
#Sta/Elev= 30
  4801.6 1722.43  4827.3 1722.10  4884.5 1722.58  4899.2 1722.00  4934.8 1722.94
  4955.7 1722.85  4976.6 1721.44  4991.3 1719.77  5003.5 1719.58  5003.8 1719.08
  5008.2 1719.08  5008.6 1719.58  5012.2 1720.10  5020.7 1719.87  5041.6 1720.98
  5056.3 1720.77  5077.2 1722.27  5098.2 1722.50  5141.7 1724.53  5187.3 1723.17
  5228.1 1722.70  5245.1 1723.01  5250.2 1723.71  5279.1 1722.97  5289.3 1723.55
  5300.9 1723.11  5319.9 1723.96  5330.2 1723.87  5351.6 1722.19  5385.7 1722.71
#Mann=3,-1,0
  4801.6    0.05       0  5003.5    0.04       0  5008.6    0.05       0
Bank Sta=5003.5,5008.6
Exp/Cntr=0.3,0.1

Type RM Length L Ch R = 1,5193,304,304,304
BEGIN DESCRIPTION:
Mapping XS 54ddafdc
END DESCRIPTION:
XS GIS Cut Line= 3
      1568715.98      6934688.25      1568560.34      6934763.39
      1568074.54      6935131.09
#Sta/Elev= 30
  4842.8 1720.81  4902.3 1720.62  4942.0 1719.36  4970.2 1719.86  4990.2 1718.78
  4990.6 1718.28  4995.0 1718.28  4995.3 1718.78  5009.8 1719.64  5050.9 1719.81
  5080.0 1718.91  5130.0 1720.87  5150.8 1719.36  5209.0 1720.29  5229.8 1719.63
  5365.1 1719.47  5386.0 1720.73  5423.3 1720.28  5429.6 1720.89  5458.7 1720.94
  5479.5 1722.45  5508.6 1722.52  5514.9 1723.42  5544.0 1724.06  5550.3 1725.14
  5558.6 1725.16  5564.8 1726.23  5573.1 1726.05  5579.4 1726.98  5624.9 1728.42
#Mann=3,-1,0
  4842.8    0.05       0  4990.2    0.04       0  4995.3    0.05       0
Bank Sta=4990.2,4995.3
Exp/Cntr=0.3,0.1

Type RM Length L Ch R = 1,4889,242,242,242
BEGIN DESCRIPTION:
Mapping XS 59738095
END DESCRIPTION:
XS GIS Cut Line= 2
      1568769.72      6934560.29      1567829.32      6934599.01
#Sta/Elev= 30
  4634.5 1721.33  4649.2 1721.64  4769.3 1718.36  4869.4 1717.55  4969.5 1717.84
  4976.9 1716.69  4977.3 1716.19  4982.1 1716.69  4999.5 1717.94  5029.6 1716.93
  5039.6 1718.15  5059.6 1718.84  5149.7 1717.86  5179.7 1718.51  5209.7 1717.74
  5249.7 1719.13  5279.8 1717.96  5299.8 1718.06  5329.8 1721.61  5349.8 1722.46
  5379.9 1721.16  5432.2 1722.42  5449.9 1724.91  5469.9 1728.80  5479.9 1729.57
  5500.0 1728.32  5520.0 1724.65  5530.0 1723.89  5550.0 1724.88  5575.7 1723.74
#Mann=3,-1,0
  4634.5    0.05       0  4976.9    0.04       0  4982.1    0.05       0
Bank Sta=4976.9,4982.1
Exp/Cntr=0.3,0.1

Type RM Length L Ch R = 1,4647,408,408,408
BEGIN DESCRIPTION:
Mapping XS 8387163d
END DESCRIPTION:
XS GIS Cut Line= 2
      1568753.13      6934432.96      1567950.36      6934228.11
#Sta/Elev= 30
  4743.7 1720.04  4762.4 1719.20  4780.9 1719.06  4803.7 1717.72  4814.0 1717.95
  4845.0 1716.88  4997.2 1715.97  4997.6 1715.47  5002.0 1715.47  5002.4 1715.97
  5026.1 1716.41  5092.7 1716.27  5102.7 1716.71  5107.8 1716.38  5113.3 1716.80
  5175.2 1717.72  5189.6 1717.37  5225.3 1718.11  5353.0 1719.11  5402.3 1720.15
  5412.6 1721.33  5434.7 1722.10  5443.6 1722.97  5470.5 1724.23  5475.6 1723.62
  5495.2 1724.15  5505.5 1723.66  5546.8 1723.71  5557.3 1723.28  5572.2 1723.66
#Mann=3,-1,0
  4743.7    0.05       0  4997.2    0.04       0  5002.4    0.05       0
Bank Sta=4997.2,5002.4
Exp/Cntr=0.3,0.1

Type RM Length L Ch R = 1,4239,409,409,409
BEGIN DESCRIPTION:
Mapping XS b2a2b8c7
END DESCRIPTION:
XS GIS Cut Line= 2
      1568969.06      6934266.88      1568155.21      6933774.13
#Sta/Elev= 30
  4604.4 1720.16  4634.8 1719.80  4650.3 1720.25  4665.8 1720.05  4671.6 1719.41
  4693.0 1719.24  4782.2 1719.43  4867.5 1716.54  4904.4 1715.95  4935.4 1716.23
  4956.7 1715.54  5004.0 1715.51  5004.4 1715.01  5008.8 1715.01  5009.2 1715.51
  5036.2 1715.83  5088.4 1717.61  5115.8 1716.98  5158.6 1717.81  5189.5 1717.21
  5217.0 1717.71  5247.7 1717.52  5342.7 1718.75  5357.3 1718.48  5428.1 1719.36
  5474.2 1719.15  5480.4 1719.57  5517.2 1719.58  5538.6 1720.29  5555.8 1720.25
#Mann=3,-1,0
  4604.4    0.05       0  5004.0    0.04       0  5009.2    0.05       0
Bank Sta=5004,5009.2
Exp/Cntr=0.3,0.1

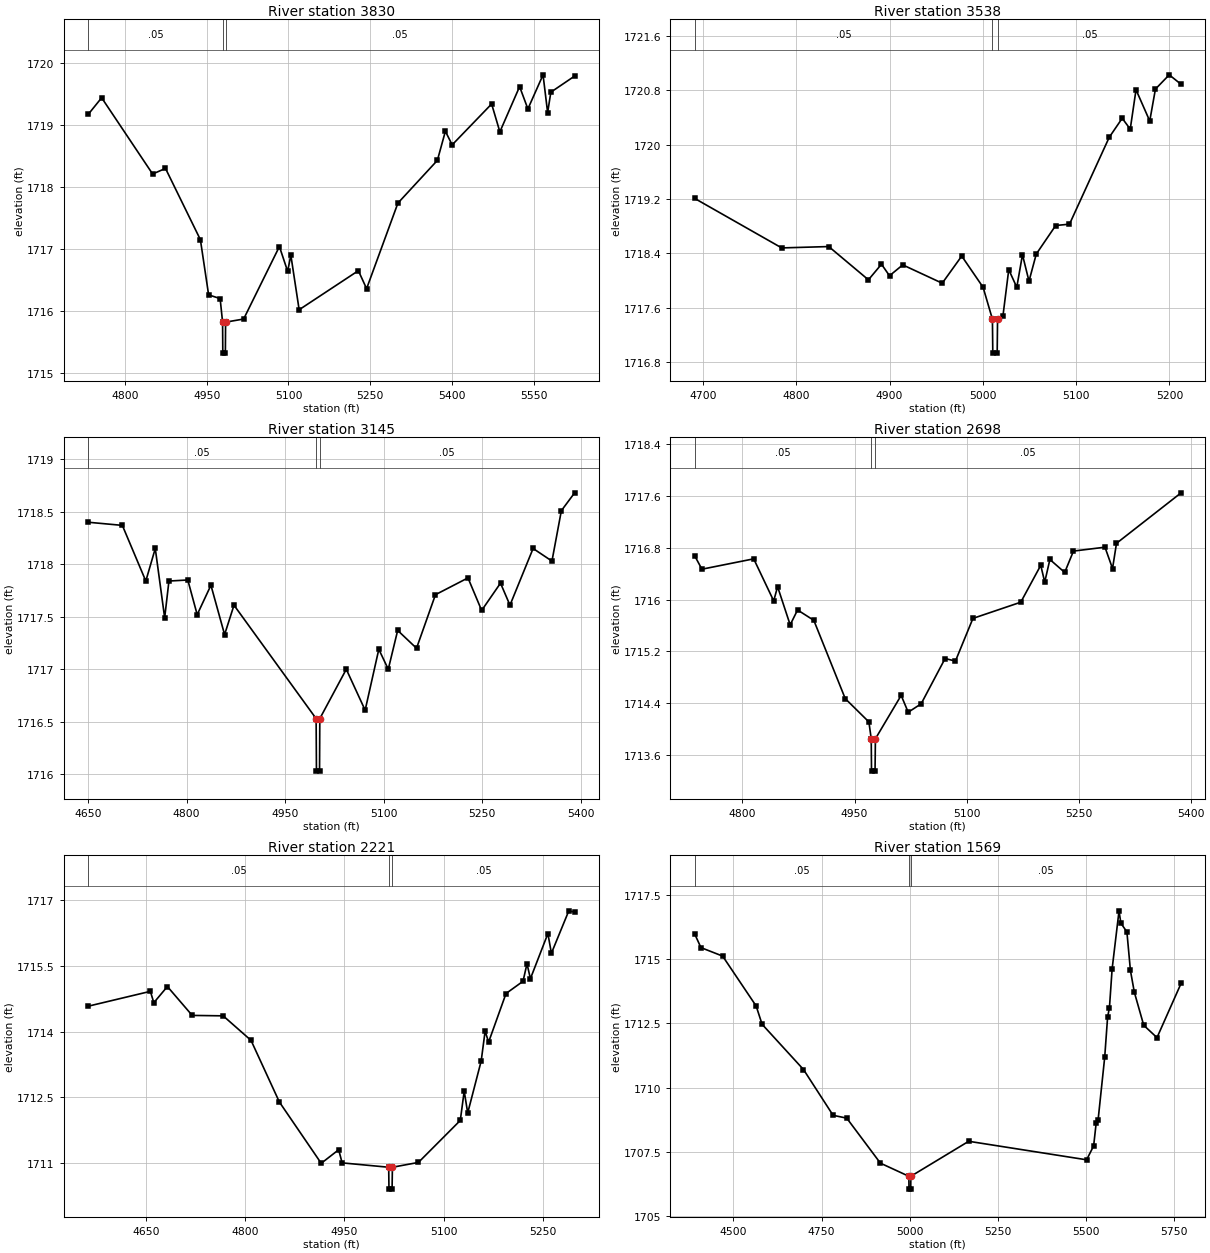
Type RM Length L Ch R = 1,3830,292,292,292
BEGIN DESCRIPTION:
Mapping XS 8e4877fc
END DESCRIPTION:
XS GIS Cut Line= 2
      1569173.89      6933984.50      1568426.46      6933497.29
#Sta/Elev= 30
  4732.6 1719.17  4757.4 1719.44  4850.9 1718.21  4874.5 1718.30  4938.5 1717.15
  4953.6 1716.26  4974.7 1716.20  4979.2 1715.82  4979.6 1715.32  4984.3 1715.32
  4984.7 1715.82  5017.8 1715.87  5083.4 1717.04  5098.5 1716.64  5104.4 1716.90
  5119.6 1716.02  5228.2 1716.65  5243.3 1716.36  5300.7 1717.74  5373.1 1718.43
  5387.8 1718.90  5400.2 1718.68  5472.6 1719.34  5487.7 1718.89  5523.9 1719.62
  5539.1 1719.26  5566.9 1719.81  5575.3 1719.20  5581.2 1719.53  5624.8 1719.79
#Mann=3,-1,0
  4732.6    0.05       0  4979.2    0.04       0  4984.7    0.05       0
Bank Sta=4979.2,4984.7
Exp/Cntr=0.3,0.1

Type RM Length L Ch R = 1,3538,393,393,393
BEGIN DESCRIPTION:
Mapping XS 49cf384b
END DESCRIPTION:
XS GIS Cut Line= 2
      1569306.49      6933756.95      1568882.39      6933453.64
#Sta/Elev= 30
  4691.1 1719.21  4784.5 1718.48  4834.9 1718.50  4877.4 1718.01  4891.4 1718.24
  4900.0 1718.07  4914.2 1718.23  4956.5 1717.96  4977.4 1718.36  5000.3 1717.90
  5010.3 1717.43  5010.7 1716.93  5015.4 1716.93  5015.8 1717.43  5021.6 1717.48
  5027.8 1718.16  5036.4 1717.90  5042.5 1718.38  5049.5 1717.99  5057.3 1718.39
  5078.1 1718.81  5092.9 1718.83  5135.5 1720.11  5149.4 1720.39  5158.0 1720.23
  5164.2 1720.81  5178.9 1720.35  5185.0 1720.82  5199.8 1721.03  5212.5 1720.89
#Mann=3,-1,0
  4691.1    0.05       0  5010.3    0.04       0  5015.8    0.05       0
Bank Sta=5010.3,5015.8
Exp/Cntr=0.3,0.1

Type RM Length L Ch R = 1,3145,447,447,447
BEGIN DESCRIPTION:
Mapping XS 37d01301
END DESCRIPTION:
XS GIS Cut Line= 2
      1569507.75      6933558.32      1569039.05      6932985.16
#Sta/Elev= 30
  4650.0 1718.40  4702.1 1718.37  4737.8 1717.84  4752.2 1718.15  4766.5 1717.49
  4773.0 1717.84  4801.7 1717.85  4816.0 1717.52  4836.9 1717.80  4857.7 1717.33
  4872.0 1717.61  4997.0 1716.53  4997.5 1716.03  5002.2 1716.03  5002.6 1716.53
  5042.9 1717.00  5071.6 1716.61  5092.4 1717.19  5106.8 1717.00  5121.1 1717.37
  5149.8 1717.20  5178.6 1717.71  5228.1 1717.87  5248.9 1717.56  5277.6 1717.82
  5292.0 1717.61  5327.2 1718.15  5355.9 1718.03  5370.2 1718.51  5390.4 1718.68
#Mann=3,-1,0
  4650.0    0.05       0  4997.0    0.04       0  5002.6    0.05       0
Bank Sta=4997,5002.6
Exp/Cntr=0.3,0.1

Type RM Length L Ch R = 1,2698,477,477,477
BEGIN DESCRIPTION:
Mapping XS ba01cf0d
END DESCRIPTION:
XS GIS Cut Line= 2
      1569743.93      6933429.50      1569543.21      6932811.27
#Sta/Elev= 30
  4736.2 1716.68  4746.0 1716.47  4815.2 1716.63  4841.9 1715.98  4847.1 1716.20
  4863.9 1715.61  4873.8 1715.84  4895.5 1715.68  4937.5 1714.47  4969.1 1714.11
  4972.2 1713.85  4972.6 1713.35  4977.3 1713.35  4977.8 1713.85  5012.2 1714.52
  5021.6 1714.26  5038.9 1714.39  5070.9 1715.09  5084.7 1715.05  5108.1 1715.71
  5172.0 1715.96  5198.7 1716.53  5204.0 1716.27  5210.9 1716.62  5230.7 1716.42
  5242.4 1716.75  5284.5 1716.81  5294.6 1716.48  5299.9 1716.87  5386.2 1717.65
#Mann=3,-1,0
  4736.2    0.05       0  4972.2    0.04       0  4977.8    0.05       0
Bank Sta=4972.2,4977.8
Exp/Cntr=0.3,0.1

Type RM Length L Ch R = 1,2221,652,652,652
BEGIN DESCRIPTION:
Mapping XS d308024c
END DESCRIPTION:
XS GIS Cut Line= 2
      1569960.05      6933541.61      1570192.57      6932844.04
#Sta/Elev= 30
  4562.8 1714.58  4656.9 1714.92  4662.1 1714.66  4682.6 1715.03  4720.1 1714.37
  4766.9 1714.36  4809.0 1713.80  4851.9 1712.39  4915.1 1710.99  4941.5 1711.30
  4946.7 1711.00  5017.1 1710.90  5017.5 1710.40  5022.2 1710.40  5022.7 1710.90
  5062.0 1711.01  5125.3 1711.97  5131.2 1712.64  5136.5 1712.14  5156.9 1713.33
  5162.8 1714.01  5168.1 1713.76  5194.4 1714.87  5220.1 1715.15  5226.1 1715.55
  5231.3 1715.21  5257.7 1716.24  5263.0 1715.79  5289.3 1716.76  5298.1 1716.73
#Mann=3,-1,0
  4562.8    0.05       0  5017.1    0.04       0  5022.7    0.05       0
Bank Sta=5017.1,5022.7
Exp/Cntr=0.3,0.1

Type RM Length L Ch R = 1,1569,646,646,646
BEGIN DESCRIPTION:
Mapping XS bc0c2e42
END DESCRIPTION:
XS GIS Cut Line= 3
      1569869.26      6933818.74      1570483.85      6933511.45
      1570691.70      6932851.54
#Sta/Elev= 30
  4390.2 1715.99  4408.2 1715.45  4469.7 1715.12  4564.7 1713.18  4581.5 1712.47
  4698.9 1710.71  4782.8 1708.93  4821.5 1708.82  4916.9 1707.07  4997.5 1706.56
  4998.0 1706.06  5002.8 1706.06  5003.2 1706.56  5167.2 1707.92  5501.4 1707.20
  5521.3 1707.74  5528.5 1708.63  5533.8 1708.73  5552.7 1711.19  5560.9 1712.75
  5566.1 1713.11  5573.7 1714.62  5593.3 1716.88  5598.5 1716.40  5615.6 1716.06
  5625.6 1714.56  5636.6 1713.72  5663.3 1712.43  5700.9 1711.95  5769.2 1714.06
#Mann=3,-1,0
  4390.2    0.05       0  4997.5    0.04       0  5003.2    0.05       0
Bank Sta=4997.5,5003.2
Exp/Cntr=0.3,0.1

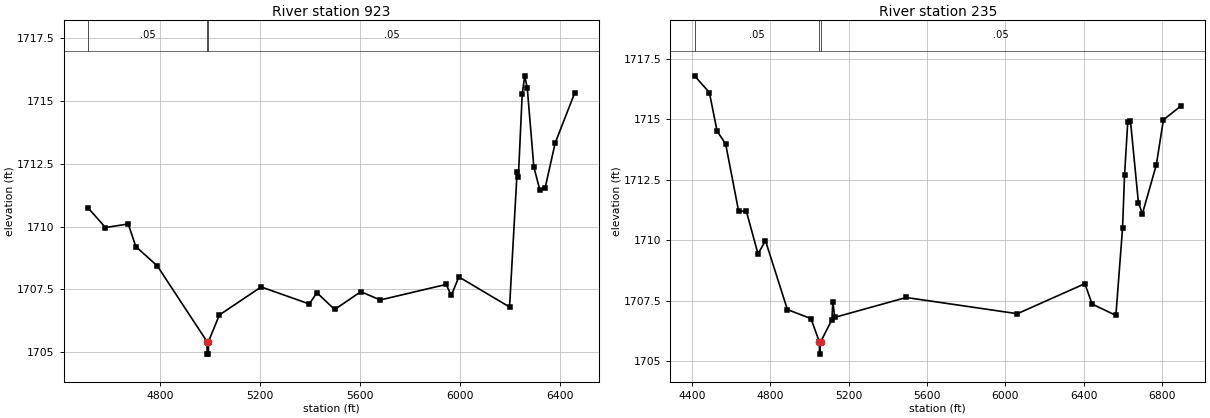
Type RM Length L Ch R = 1,923,688,688,688
BEGIN DESCRIPTION:
Mapping XS a7851d15
END DESCRIPTION:
XS GIS Cut Line= 3
      1569926.52      6934204.16      1570582.81      6934105.20
      1570785.66      6932841.28
#Sta/Elev= 30
  4513.0 1710.74  4582.3 1709.96  4673.3 1710.10  4703.6 1709.20  4789.3 1708.43
  4988.1 1705.41  4988.6 1704.91  4993.5 1704.91  4993.9 1705.41  5037.3 1706.47
  5204.3 1707.59  5396.7 1706.91  5427.1 1707.36  5498.0 1706.69  5602.5 1707.40
  5680.3 1707.07  5943.6 1707.69  5963.9 1707.25  5994.2 1707.99  6196.8 1706.79
  6226.9 1712.16  6232.0 1711.97  6247.4 1715.28  6257.6 1716.01  6267.7 1715.51
  6293.9 1712.37  6318.3 1711.44  6338.6 1711.52  6379.1 1713.33  6456.8 1715.32
#Mann=3,-1,0
  4513.0    0.05       0  4988.1    0.04       0  4993.9    0.05       0
Bank Sta=4988.1,4993.9
Exp/Cntr=0.3,0.1

Type RM Length L Ch R = 1,235,0,0,0
BEGIN DESCRIPTION:
Deadman 30 1.0
END DESCRIPTION:
XS GIS Cut Line= 3
      1570070.79      6934964.45      1570502.63      6934765.14
      1570834.81      6932783.10
#Sta/Elev= 30
  4412.7 1716.79  4488.3 1716.10  4527.5 1714.51  4571.5 1713.97  4637.6 1711.20
  4677.4 1711.19  4736.7 1709.43  4774.7 1709.98  4886.9 1707.13  5007.1 1706.76
  5050.4 1705.79  5050.9 1705.29  5056.3 1705.79  5114.0 1706.71  5119.0 1707.45
  5128.8 1706.81  5493.8 1707.63  6061.6 1706.96  6406.3 1708.20  6443.6 1707.36
  6564.9 1706.89  6599.0 1710.50  6609.1 1712.68  6625.6 1714.90  6639.5 1714.92
  6680.1 1711.54  6700.4 1711.09  6771.4 1713.11  6807.6 1714.97  6898.0 1715.55
#Mann=3,-1,0
  4412.7    0.05       0  5050.4    0.04       0  5056.3    0.05       0
Bank Sta=5050.4,5056.3
Exp/Cntr=0.3,0.1

Chan Stop Cuts=-1