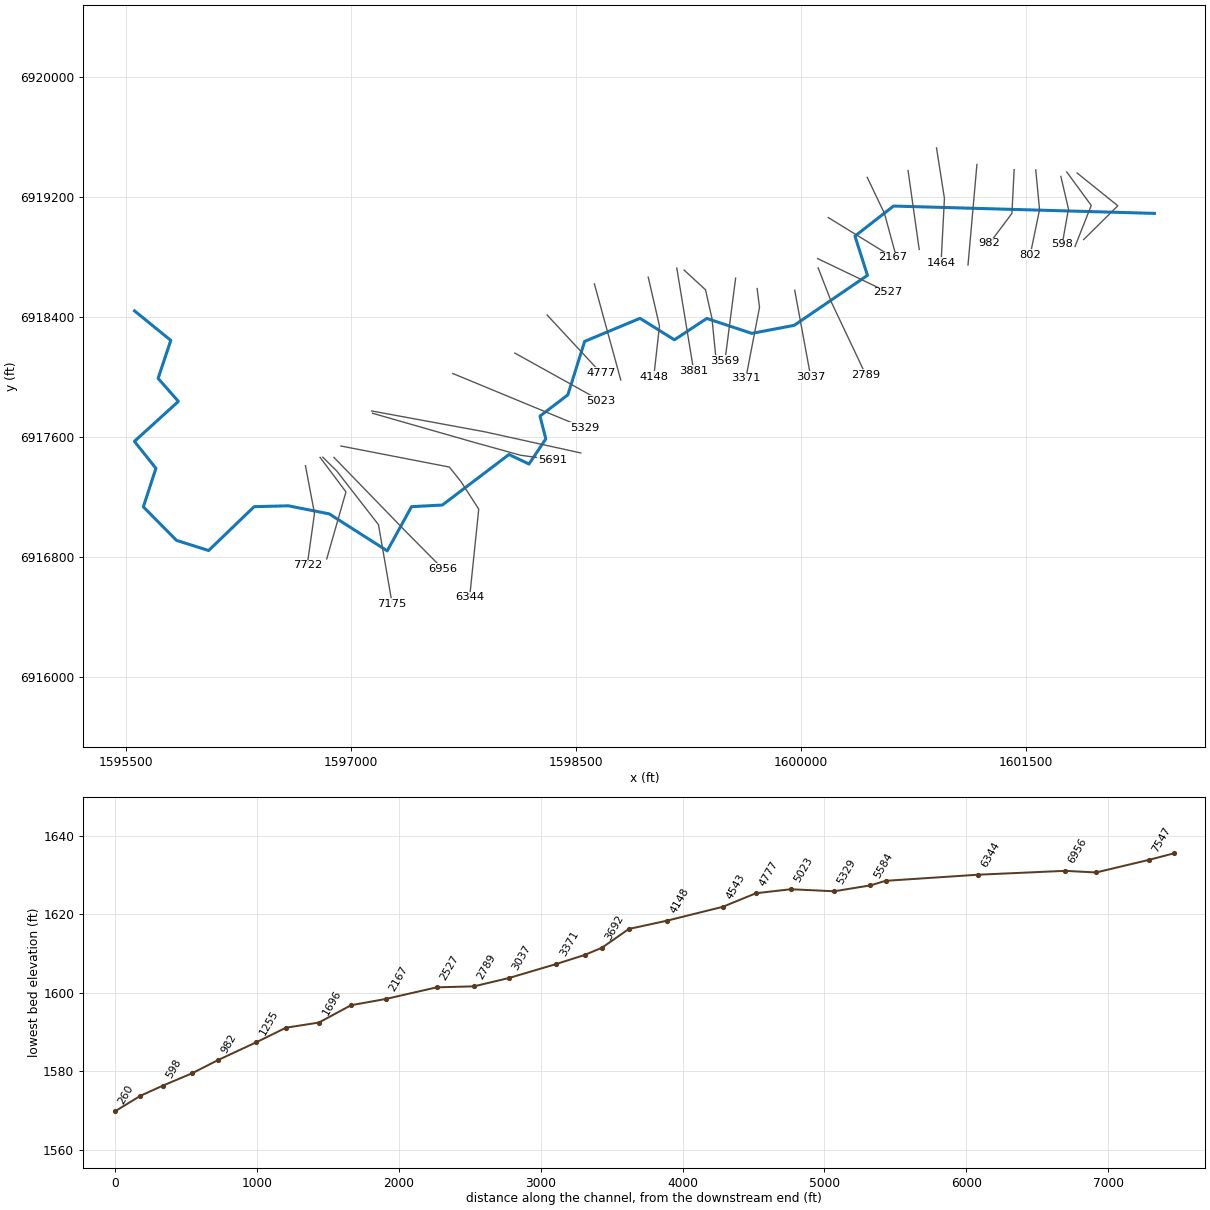
--- Deadman 33.prj (project) ---

Proj Title=Deadman 33 Base Level Engineering
Current Plan=p01
Default Exp/Contr=0.3,0.1
English Units
Geom File=g01
Flow File=f01
Plan File=p01
BEGIN DESCRIPTION:
Deadman 33
END DESCRIPTION:

--- Deadman 33.p01 (plan) ---

Plan Title=Multiple Run
Short Identifier=Multiple
Geom File=g01
Flow File=f01
Subcritical Flow
K Sum by GR= 0
Std Step Tol= 0.01
Critical Tol= 0.01
Num of Std Step Trials= 20
Max Error Tol= 0.3
Flow Tol Ratio= 0.001
Split Flow NTrial= 30
Split Flow Tol= 0.02
Split Flow Ratio= 0.02
Log Output Level= 0
Friction Slope Method= 1
Unsteady Friction Slope Method= 2
Unsteady Bridges Friction Slope Method= 1
Parabolic Critical Depth
Global Vel Dist=  1 , 1 , 1
Global Log Level= 0
CheckData=True
Encroach Param= -1, 0, 0, 0
BEGIN DESCRIPTION:
Multiple Run
END DESCRIPTION:

--- Deadman 33.f01 (steady flow) ---

Flow Title=Multiple
Number of Profiles=7
Profile Names=10-year,25-year,50-year,1pct_min,100-year,1pct_plu,500-year
River Rch & RM= Deadman 33,Reach-1,7722
     221     299     362     218     434     867     634
River Rch & RM= Deadman 33,Reach-1,2167
     307     425     521     318     634    1266     952
Boundary for River Rch & Prof#=Deadman 33,Reach-1,1
Up Type=0
Dn Type=3
Dn Slope=0.007
Boundary for River Rch & Prof#=Deadman 33,Reach-1,2
Up Type=0
Dn Type=3
Dn Slope=0.007
Boundary for River Rch & Prof#=Deadman 33,Reach-1,3
Up Type=0
Dn Type=3
Dn Slope=0.007
Boundary for River Rch & Prof#=Deadman 33,Reach-1,4
Up Type=0
Dn Type=3
Dn Slope=0.007
Boundary for River Rch & Prof#=Deadman 33,Reach-1,5
Up Type=0
Dn Type=3
Dn Slope=0.007
Boundary for River Rch & Prof#=Deadman 33,Reach-1,6
Up Type=0
Dn Type=3
Dn Slope=0.007
Boundary for River Rch & Prof#=Deadman 33,Reach-1,7
Up Type=0
Dn Type=3
Dn Slope=0.007

--- Deadman 33.g01 (geometry) ---

Geom Title=Existing Conditions

River Reach=Deadman 33,Reach-1
Reach XY= 30
      1595555.00      6918438.00      1595797.02      6918241.33
      1595712.29      6917987.91      1595847.48      6917834.43
      1595554.31      6917567.94      1595697.65      6917388.09
      1595613.97      6917131.33      1595834.91      6916907.78
      1596049.04      6916840.14      1596352.55      6917132.54
      1596580.12      6917138.29      1596853.50      6917084.53
      1597239.79      6916837.89      1597402.00      6917132.54
      1597607.47      6917143.45      1598051.67      6917480.39
      1598185.21      6917416.93      1598297.19      6917584.59
      1598258.46      6917736.51      1598443.89      6917877.68
      1598556.25      6918234.55      1598925.10      6918388.11
      1599154.79      6918245.02      1599370.21      6918387.50
      1599670.34      6918287.96      1599953.53      6918341.55
      1600441.89      6918674.79      1600358.46      6918936.50
      1600615.55      6919136.91      1602355.00      6919088.00

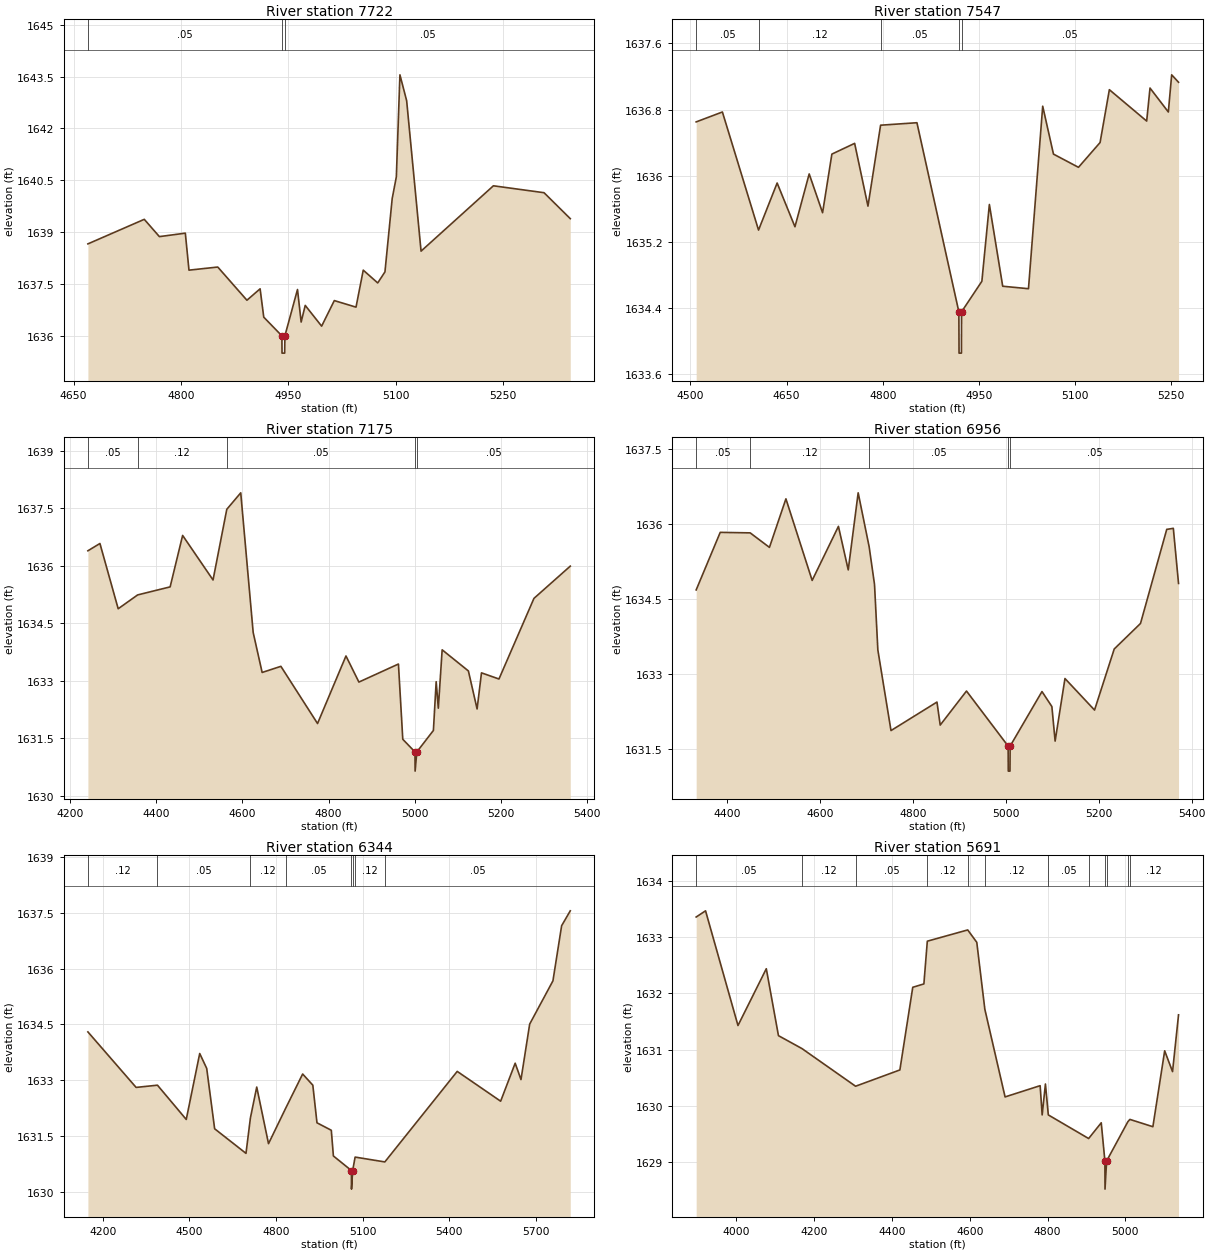
Type RM Length L Ch R = 1,7722,175,175,175
BEGIN DESCRIPTION:
Deadman 33 12.0
END DESCRIPTION:
XS GIS Cut Line= 3
      1596694.50      6917406.06      1596755.00      6917088.00
      1596706.24      6916741.78
#Sta/Elev= 30
  4670.0 1638.66  4748.7 1639.37  4769.8 1638.87  4806.0 1638.97  4811.1 1637.90
  4851.3 1637.99  4892.0 1637.03  4910.4 1637.36  4915.5 1636.54  4940.8 1636.00
  4941.0 1635.50  4944.7 1635.50  4945.0 1636.00  4962.6 1637.34  4967.7 1636.40
  4973.4 1636.88  4996.3 1636.28  5014.0 1637.02  5044.3 1636.83  5054.4 1637.90
  5074.6 1637.53  5084.7 1637.85  5094.8 1639.97  5100.6 1640.60  5105.6 1643.55
  5115.0 1642.80  5135.1 1638.45  5236.1 1640.34  5306.8 1640.14  5343.4 1639.39
#Mann=3,-1,0
  4670.0    0.05       0  4940.8    0.03       0  4945.0    0.05       0
Bank Sta=4940.8,4945
Exp/Cntr=0.3,0.1

Type RM Length L Ch R = 1,7547,372,372,372
BEGIN DESCRIPTION:
Mapping XS f760b5e4
END DESCRIPTION:
XS GIS Cut Line= 3
      1596792.06      6917461.26      1596964.65      6917231.39
      1596836.60      6916784.31
#Sta/Elev= 30
  4508.9 1636.65  4549.8 1636.77  4606.2 1635.34  4635.2 1635.91  4663.0 1635.38
  4685.2 1636.02  4706.1 1635.55  4720.6 1636.26  4756.1 1636.39  4776.9 1635.63
  4796.6 1636.61  4853.3 1636.64  4918.7 1634.35  4919.0 1633.85  4922.7 1633.85
  4922.9 1634.35  4954.6 1634.72  4966.3 1635.65  4987.1 1634.66  5027.3 1634.63
  5049.5 1636.84  5066.3 1636.26  5105.3 1636.10  5139.0 1636.40  5153.5 1637.04
  5211.7 1636.66  5216.9 1637.06  5245.5 1636.77  5250.7 1637.22  5261.4 1637.13
#Mann=5,-1,0
  4508.9    0.05       0  4606.2    0.12       0  4796.6    0.05       0
  4918.7    0.05       0  4922.9    0.05       0
Bank Sta=4918.7,4922.9
Exp/Cntr=0.3,0.1

Type RM Length L Ch R = 1,7175,219,219,219
BEGIN DESCRIPTION:
Mapping XS 09ffdbde
END DESCRIPTION:
XS GIS Cut Line= 4
      1596810.14      6917462.57      1596904.30      6917369.24
      1597181.66      6917012.21      1597272.80      6916484.91
#Sta/Elev= 30
  4241.4 1636.39  4269.3 1636.58  4311.7 1634.88  4356.8 1635.24  4432.3 1635.45
  4461.3 1636.79  4531.9 1635.63  4563.8 1637.47  4596.2 1637.90  4625.1 1634.26
  4645.9 1633.22  4689.4 1633.38  4774.5 1631.89  4840.5 1633.65  4870.5 1632.97
  4962.3 1633.44  4972.4 1631.48  5000.7 1631.15  5001.0 1630.65  5005.0 1631.15
  5043.5 1631.71  5049.9 1632.98  5054.9 1632.29  5063.8 1633.81  5124.7 1633.26
  5144.9 1632.27  5155.1 1633.21  5195.7 1633.05  5276.9 1635.15  5361.2 1635.99
#Mann=5,-1,0
  4241.4    0.05       0  4356.8    0.12       0  4563.8    0.05       0
  5000.7    0.03       0  5005.0    0.05       0
Bank Sta=5000.7,5005
Exp/Cntr=0.3,0.1

Type RM Length L Ch R = 1,6956,612,612,612
BEGIN DESCRIPTION:
Deadman 33 11.0
END DESCRIPTION:
XS GIS Cut Line= 3
      1596884.73      6917460.97      1597366.12      6916964.46
      1597610.64      6916717.78
#Sta/Elev= 30
  4332.9 1634.68  4384.7 1635.83  4449.2 1635.82  4490.7 1635.53  4526.2 1636.50
  4582.7 1634.87  4639.3 1635.95  4660.4 1635.08  4681.8 1636.62  4705.5 1635.54
  4717.0 1634.79  4724.2 1633.48  4752.5 1631.87  4851.5 1632.44  4858.5 1631.98
  4915.1 1632.66  5004.8 1631.56  5005.1 1631.06  5008.8 1631.06  5009.1 1631.56
  5077.7 1632.65  5099.0 1632.35  5106.0 1631.66  5127.2 1632.91  5190.9 1632.28
  5233.3 1633.50  5289.9 1634.01  5346.4 1635.89  5360.6 1635.91  5371.8 1634.81
#Mann=5,-1,0
  4332.9    0.05       0  4449.2    0.12       0  4705.5    0.05       0
  5004.8    0.05       0  5009.1    0.05       0
Bank Sta=5004.8,5009.1
Exp/Cntr=0.3,0.1

Type RM Length L Ch R = 1,6344,653,653,653
BEGIN DESCRIPTION:
Deadman 33 10.0
END DESCRIPTION:
XS GIS Cut Line= 5
      1596931.19      6917536.98      1597654.00      6917396.71
      1597730.70      6917300.83      1597850.06      6917116.37
      1597789.30      6916528.29
#Sta/Elev= 30
  4148.8 1634.30  4315.7 1632.81  4389.6 1632.87  4489.3 1631.95  4535.9 1633.72
  4560.1 1633.32  4587.6 1631.70  4696.1 1631.04  4711.4 1631.99  4733.3 1632.82
  4774.1 1631.30  4834.1 1632.26  4892.3 1633.17  4927.5 1632.87  4941.9 1631.86
  4991.5 1631.66  4998.7 1630.97  5061.1 1630.58  5061.4 1630.08  5065.5 1630.58
  5073.9 1630.94  5176.8 1630.81  5427.4 1633.24  5577.8 1632.44  5628.1 1633.46
  5648.2 1633.02  5678.3 1634.51  5758.8 1635.67  5788.9 1637.15  5818.8 1637.55
#Mann=8,-1,0
  4148.8    0.12       0  4389.6    0.05       0  4711.4    0.12       0
  4834.1    0.05       0  5061.1    0.05       0  5065.5    0.05       0
  5073.9    0.12       0  5176.8    0.05       0
Bank Sta=5061.1,5065.5
Exp/Cntr=0.3,0.1

Type RM Length L Ch R = 1,5691,107,107,107
BEGIN DESCRIPTION:
Deadman 33 9.0
END DESCRIPTION:
XS GIS Cut Line= 4
      1597141.79      6917755.31      1597811.06      6917563.63
      1598128.96      6917475.50      1598340.28      6917446.27
#Sta/Elev= 30
  3897.2 1633.36  3921.3 1633.47  4004.6 1631.43  4077.4 1632.44  4108.6 1631.25
  4169.0 1631.02  4306.8 1630.35  4420.6 1630.64  4453.7 1632.11  4482.3 1632.17
  4491.1 1632.93  4594.9 1633.13  4618.2 1632.91  4638.9 1631.72  4690.9 1630.16
  4781.0 1630.36  4786.2 1629.84  4794.6 1630.39  4802.0 1629.84  4905.6 1629.42
  4938.0 1629.70  4947.4 1629.02  4947.7 1628.52  4951.8 1629.02  5006.5 1629.72
  5011.7 1629.76  5070.7 1629.63  5101.0 1630.98  5121.2 1630.61  5136.6 1631.62
#Mann=12,-1,0
  3897.2    0.05       0  4169.0    0.12       0  4306.8    0.05       0
  4491.1    0.12       0  4594.9    0.05       0  4638.9    0.12       0
  4802.0    0.05       0  4905.6    0.12       0  4947.4    0.07       0
  4951.8    0.12       0  5006.5    0.05       0  5011.7    0.12       0
Bank Sta=4947.4,4951.8
Exp/Cntr=0.3,0.1

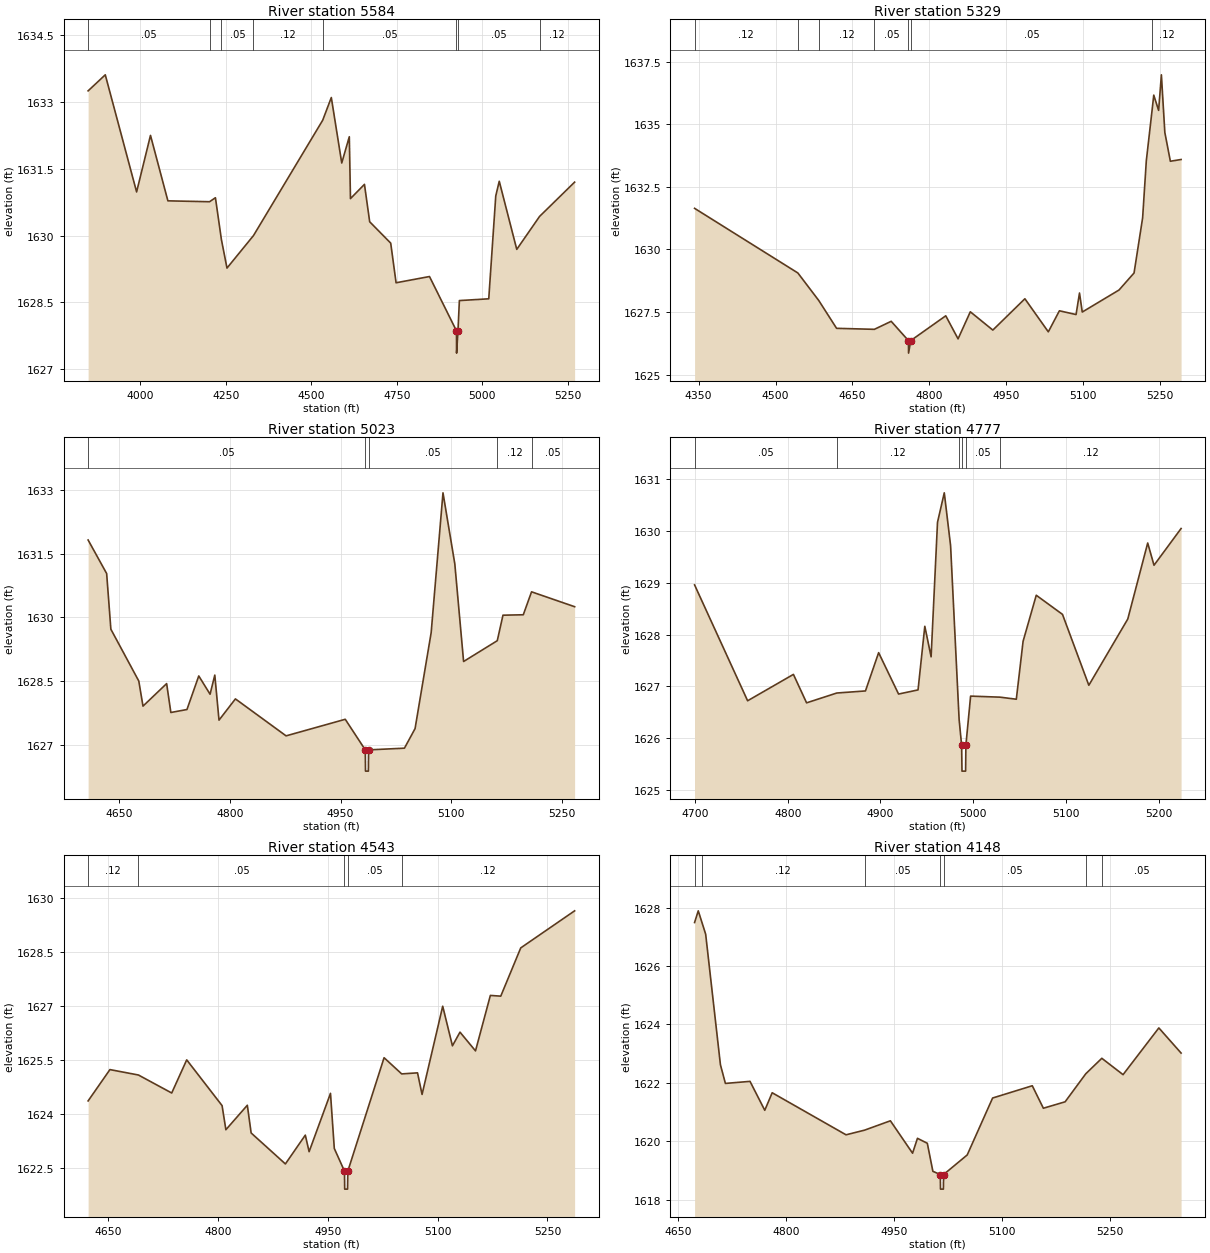
Type RM Length L Ch R = 1,5584,255,255,255
BEGIN DESCRIPTION:
Deadman 33 8.0
END DESCRIPTION:
XS GIS Cut Line= 3
      1597135.58      6917770.79      1597890.24      6917631.75
      1598530.23      6917490.74
#Sta/Elev= 30
  3847.0 1633.25  3897.2 1633.61  3988.8 1630.98  4029.4 1632.25  4080.3 1630.78
  4202.1 1630.76  4219.3 1630.85  4236.8 1629.91  4253.1 1629.27  4330.6 1630.00
  4533.0 1632.59  4558.2 1633.10  4588.7 1631.63  4610.8 1632.22  4614.2 1630.83
  4655.1 1631.15  4670.4 1630.31  4731.9 1629.83  4747.6 1628.94  4845.3 1629.08
  4924.2 1627.86  4924.5 1627.36  4928.6 1627.86  4932.7 1628.54  5018.6 1628.58
  5039.1 1630.89  5049.3 1631.22  5100.5 1629.69  5167.2 1630.43  5269.7 1631.20
#Mann=8,-1,0
  3847.0    0.05       0  4202.1    0.12       0  4236.8    0.05       0
  4330.6    0.12       0  4533.0    0.05       0  4924.2    0.05       0
  4928.6    0.05       0  5167.2    0.12       0
Bank Sta=4924.2,4928.6
Exp/Cntr=0.3,0.1

Type RM Length L Ch R = 1,5329,306,306,306
BEGIN DESCRIPTION:
Mapping XS 6421fe22
END DESCRIPTION:
XS GIS Cut Line= 2
      1597677.53      6918020.22      1598554.28      6917657.80
#Sta/Elev= 30
  4342.1 1631.64  4543.5 1629.06  4584.3 1627.96  4619.0 1626.85  4692.7 1626.81
  4725.5 1627.13  4759.1 1626.36  4759.4 1625.86  4763.6 1626.36  4831.9 1627.35
  4855.9 1626.43  4879.8 1627.51  4923.7 1626.78  4986.2 1628.03  5031.9 1626.71
  5053.5 1627.55  5086.0 1627.40  5092.7 1628.26  5098.1 1627.50  5169.8 1628.38
  5199.1 1629.06  5215.8 1631.26  5223.0 1633.54  5234.7 1635.64  5237.5 1636.16
  5247.0 1635.55  5252.4 1636.97  5259.1 1634.67  5269.9 1633.52  5290.8 1633.59
#Mann=7,-1,0
  4342.1    0.12       0  4543.5    0.05       0  4584.3    0.12       0
  4692.7    0.05       0  4759.1    0.03       0  4763.6    0.05       0
  5234.7    0.12       0
Bank Sta=4759.1,4763.6
Exp/Cntr=0.3,0.1

Type RM Length L Ch R = 1,5023,246,246,246
BEGIN DESCRIPTION:
Mapping XS 012b16a0
END DESCRIPTION:
XS GIS Cut Line= 2
      1598090.69      6918156.65      1598666.41      6917836.80
#Sta/Elev= 30
  4608.2 1631.82  4633.3 1631.03  4639.0 1629.72  4676.8 1628.50  4682.5 1627.91
  4714.5 1628.44  4720.2 1627.76  4742.0 1627.83  4758.0 1628.62  4773.3 1628.19
  4779.7 1628.64  4785.4 1627.58  4807.6 1628.08  4876.2 1627.21  4956.3 1627.60
  4983.4 1626.88  4983.7 1626.38  4987.6 1626.38  4987.9 1626.88  5036.4 1626.92
  5050.8 1627.38  5072.6 1629.64  5088.6 1632.93  5104.6 1631.26  5116.5 1628.96
  5162.1 1629.45  5169.8 1630.05  5197.3 1630.06  5208.5 1630.60  5266.8 1630.25
#Mann=5,-1,0
  4608.2    0.05       0  4983.4    0.05       0  4987.9    0.05       0
  5162.1    0.12       0  5208.5    0.05       0
Bank Sta=4983.4,4987.9
Exp/Cntr=0.3,0.1

Type RM Length L Ch R = 1,4777,234,234,234
BEGIN DESCRIPTION:
Mapping XS 9aac2122
END DESCRIPTION:
XS GIS Cut Line= 2
      1598306.30      6918409.89      1598663.56      6918025.61
#Sta/Elev= 30
  4699.5 1628.96  4756.7 1626.72  4806.1 1627.23  4820.3 1626.68  4852.9 1626.87
  4883.8 1626.91  4898.0 1627.65  4919.5 1626.85  4940.5 1626.93  4947.8 1628.16
  4954.6 1627.57  4961.5 1630.17  4968.8 1630.74  4975.6 1629.72  4984.8 1626.36
  4987.5 1625.86  4987.9 1625.36  4991.8 1625.36  4992.1 1625.86  4997.2 1626.81
  5028.8 1626.79  5046.5 1626.75  5053.8 1627.87  5068.0 1628.76  5096.3 1628.39
  5124.7 1627.02  5166.7 1628.30  5188.2 1629.77  5195.0 1629.34  5224.2 1630.05
#Mann=6,-1,0
  4699.5    0.05       0  4852.9    0.12       0  4984.8    0.05       0
  4987.5    0.05       0  4992.1    0.05       0  5028.8    0.12       0
Bank Sta=4987.5,4992.1
Exp/Cntr=0.3,0.1

Type RM Length L Ch R = 1,4543,395,395,395
BEGIN DESCRIPTION:
Mapping XS 03e0a437
END DESCRIPTION:
XS GIS Cut Line= 2
      1598621.06      6918617.88      1598797.12      6917977.02
#Sta/Elev= 30
  4622.6 1624.35  4652.4 1625.22  4691.3 1625.07  4736.8 1624.57  4757.3 1625.49
  4805.6 1624.22  4810.8 1623.55  4840.1 1624.23  4845.3 1623.46  4892.1 1622.60
  4919.3 1623.40  4924.5 1622.94  4953.7 1624.56  4958.9 1623.03  4972.8 1622.40
  4973.1 1621.90  4977.0 1621.90  4977.4 1622.40  5026.9 1625.55  5051.0 1625.10
  5072.6 1625.13  5078.8 1624.53  5107.0 1626.98  5120.3 1625.88  5130.6 1626.26
  5151.8 1625.74  5172.1 1627.28  5186.3 1627.26  5213.6 1628.60  5287.2 1629.63
#Mann=5,-1,0
  4622.6    0.12       0  4691.3    0.05       0  4972.8    0.05       0
  4977.4    0.05       0  5051.0    0.12       0
Bank Sta=4972.8,4977.4
Exp/Cntr=0.3,0.1

Type RM Length L Ch R = 1,4148,267,267,267
BEGIN DESCRIPTION:
Deadman 33 7.0
END DESCRIPTION:
XS GIS Cut Line= 3
      1598980.00      6918663.01      1599055.00      6918338.00
      1599017.06      6917997.86
#Sta/Elev= 30
  4672.8 1627.49  4677.9 1627.89  4683.2 1627.48  4688.2 1627.09  4708.7 1622.62
  4715.6 1621.98  4749.8 1622.05  4770.3 1621.06  4780.6 1621.66  4883.2 1620.22
  4909.0 1620.38  4944.8 1620.70  4975.6 1619.59  4982.4 1620.10  4996.1 1619.93
  5003.8 1618.97  5014.1 1618.86  5014.4 1618.36  5018.4 1618.36  5018.7 1618.86
  5051.5 1619.53  5086.8 1621.48  5141.9 1621.90  5157.3 1621.13  5187.5 1621.35
  5216.2 1622.31  5238.5 1622.84  5268.0 1622.28  5317.7 1623.88  5348.6 1623.02
#Mann=7,-1,0
  4672.8    0.05       0  4683.2    0.12       0  4909.0    0.05       0
  5014.1    0.05       0  5018.7    0.05       0  5216.2    0.12       0
  5238.5    0.05       0
Bank Sta=5014.1,5018.7
Exp/Cntr=0.3,0.1

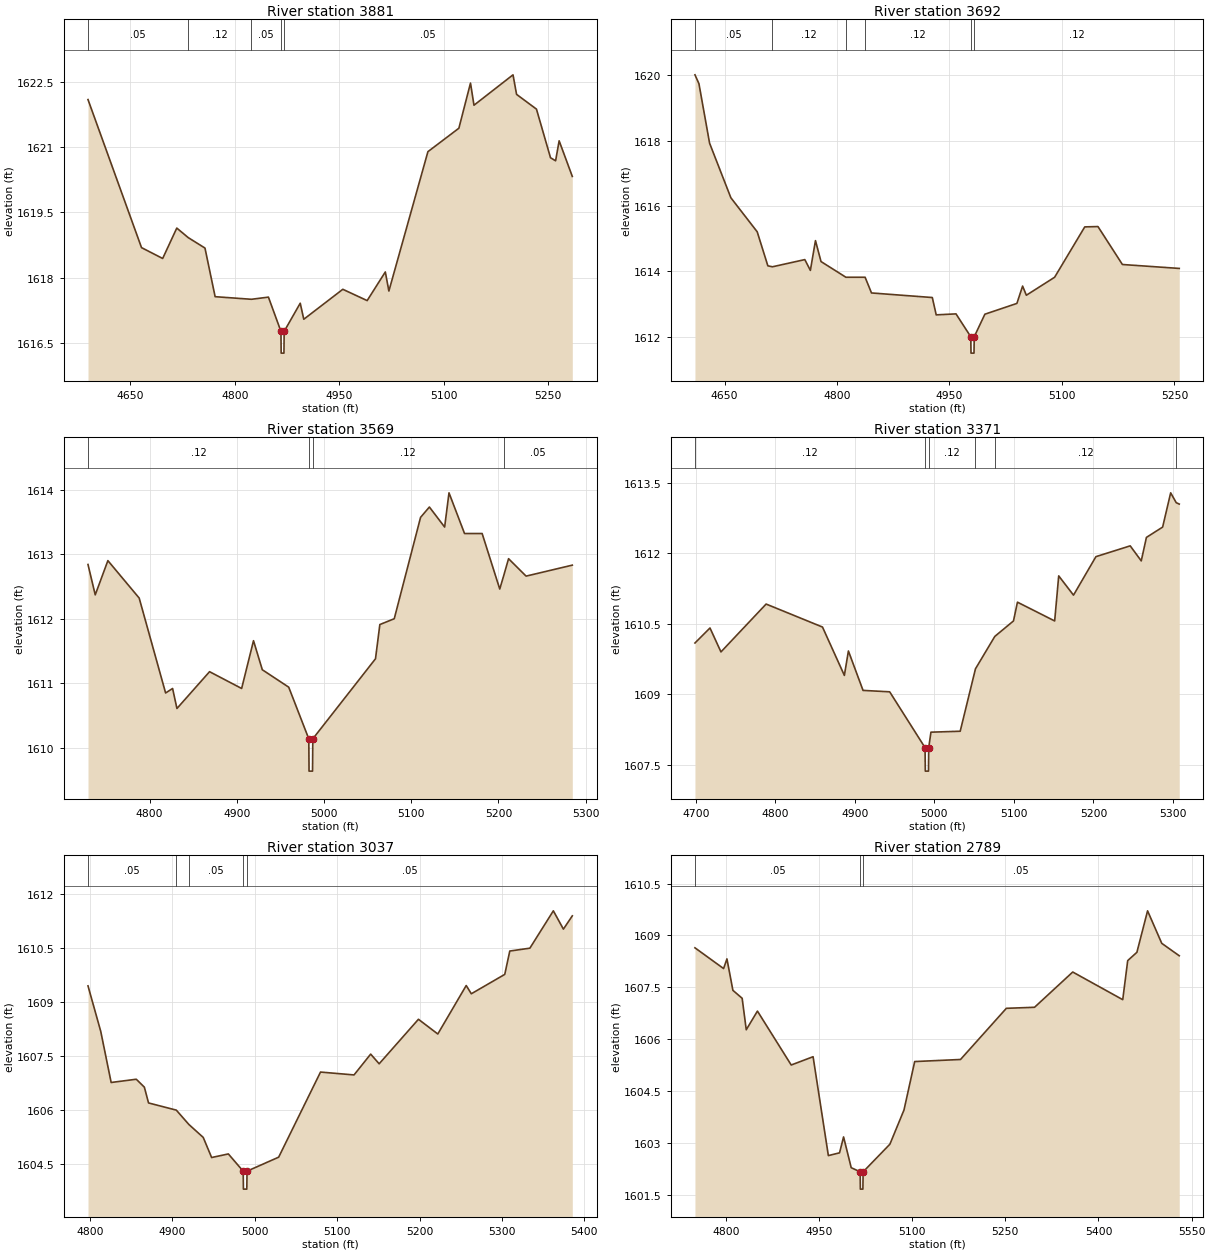
Type RM Length L Ch R = 1,3881,189,189,189
BEGIN DESCRIPTION:
Mapping XS 467cc73c
END DESCRIPTION:
XS GIS Cut Line= 2
      1599170.41      6918723.89      1599283.54      6918037.15
#Sta/Elev= 30
  4589.0 1622.10  4665.9 1618.69  4696.3 1618.44  4716.6 1619.14  4733.1 1618.92
  4757.1 1618.68  4771.7 1617.56  4823.9 1617.50  4848.3 1617.55  4866.3 1616.76
  4866.6 1616.26  4870.6 1616.26  4870.9 1616.76  4894.0 1617.41  4899.1 1617.04
  4955.2 1617.73  4990.2 1617.47  5016.3 1618.13  5021.4 1617.69  5077.5 1620.90
  5122.0 1621.44  5138.7 1622.48  5143.7 1621.97  5199.8 1622.67  5204.9 1622.22
  5233.5 1621.88  5253.7 1620.76  5261.0 1620.69  5266.1 1621.15  5285.0 1620.33
#Mann=5,-1,0
  4589.0    0.05       0  4733.1    0.12       0  4823.9    0.05       0
  4866.3    0.05       0  4870.9    0.05       0
Bank Sta=4866.3,4870.9
Exp/Cntr=0.3,0.1

Type RM Length L Ch R = 1,3692,123,123,123
BEGIN DESCRIPTION:
Deadman 33 6.0
END DESCRIPTION:
XS GIS Cut Line= 4
      1599219.47      6918709.72      1599362.09      6918578.67
      1599405.00      6918388.00      1599430.54      6918132.60
#Sta/Elev= 30
  4610.6 1620.01  4615.9 1619.74  4630.1 1617.92  4658.5 1616.25  4693.6 1615.21
  4707.8 1614.17  4713.9 1614.14  4757.1 1614.36  4764.5 1614.03  4771.3 1614.94
  4778.7 1614.30  4811.9 1613.82  4837.5 1613.82  4846.0 1613.34  4927.1 1613.20
  4932.3 1612.67  4958.7 1612.70  4978.4 1612.00  4978.7 1611.50  4982.7 1611.50
  4983.0 1612.00  4997.2 1612.69  5039.9 1613.02  5047.5 1613.55  5052.5 1613.27
  5090.2 1613.82  5130.4 1615.36  5148.0 1615.37  5180.6 1614.21  5256.4 1614.09
#Mann=6,-1,0
  4610.6    0.05       0  4713.9    0.12       0  4811.9    0.05       0
  4837.5    0.12       0  4978.4    0.07       0  4983.0    0.12       0
Bank Sta=4978.4,4983
Exp/Cntr=0.3,0.1

Type RM Length L Ch R = 1,3569,198,198,198
BEGIN DESCRIPTION:
Mapping XS d04cad1e
END DESCRIPTION:
XS GIS Cut Line= 2
      1599562.84      6918656.25      1599491.48      6918105.46
#Sta/Elev= 30
  4729.3 1612.84  4737.6 1612.37  4752.1 1612.90  4788.0 1612.32  4818.3 1610.85
  4826.3 1610.92  4831.3 1610.61  4868.7 1611.18  4905.5 1610.92  4919.1 1611.66
  4929.2 1611.21  4959.5 1610.94  4982.5 1610.14  4982.8 1609.64  4986.8 1609.64
  4987.1 1610.14  5059.0 1611.38  5064.0 1611.91  5080.5 1612.00  5110.7 1613.57
  5120.8 1613.73  5138.3 1613.42  5143.3 1613.95  5161.1 1613.32  5181.3 1613.32
  5201.5 1612.46  5206.1 1612.67  5211.6 1612.93  5231.7 1612.66  5284.7 1612.83
#Mann=4,-1,0
  4729.3    0.12       0  4982.5    0.07       0  4987.1    0.12       0
  5206.1    0.05       0
Bank Sta=4982.5,4987.1
Exp/Cntr=0.3,0.1

Type RM Length L Ch R = 1,3371,334,334,334
BEGIN DESCRIPTION:
Mapping XS c1c8234a
END DESCRIPTION:
XS GIS Cut Line= 3
      1599706.01      6918586.79      1599722.04      6918461.57
      1599630.70      6917987.43
#Sta/Elev= 30
  4698.9 1610.09  4717.8 1610.41  4731.6 1609.90  4788.4 1610.92  4859.3 1610.43
  4886.8 1609.40  4891.9 1609.92  4910.3 1609.08  4943.8 1609.05  4988.3 1607.86
  4988.6 1607.36  4992.6 1607.36  4992.9 1607.86  4995.7 1608.19  5032.5 1608.21
  5051.7 1609.54  5076.0 1610.23  5099.5 1610.56  5104.5 1610.96  5151.3 1610.56
  5156.4 1611.52  5175.0 1611.11  5203.2 1611.93  5246.3 1612.16  5260.2 1611.84
  5266.7 1612.34  5287.1 1612.56  5297.2 1613.29  5304.2 1613.08  5308.0 1613.05
#Mann=6,-1,0
  4698.9    0.12       0  4988.3    0.07       0  4992.9    0.12       0
  5051.7    0.05       0  5076.0    0.12       0  5304.2    0.05       0
Bank Sta=4988.3,4992.9
Exp/Cntr=0.3,0.1

Type RM Length L Ch R = 1,3037,248,248,248
BEGIN DESCRIPTION:
Mapping XS 81491553
END DESCRIPTION:
XS GIS Cut Line= 2
      1599956.68      6918575.59      1600063.63      6917997.40
#Sta/Elev= 30
  4797.5 1609.45  4813.0 1608.18  4825.6 1606.76  4856.1 1606.85  4865.9 1606.63
  4871.0 1606.19  4904.7 1605.99  4920.0 1605.59  4937.4 1605.23  4947.6 1604.67
  4967.9 1604.77  4985.9 1604.29  4986.2 1603.79  4990.3 1603.79  4990.6 1604.29
  5029.0 1604.68  5079.8 1607.05  5120.5 1606.97  5140.7 1607.55  5151.0 1607.28
  5198.7 1608.52  5222.2 1608.11  5256.7 1609.46  5262.9 1609.23  5303.5 1609.77
  5309.6 1610.42  5334.0 1610.50  5362.5 1611.54  5374.7 1611.03  5385.5 1611.40
#Mann=5,-1,0
  4797.5    0.05       0  4904.7    0.12       0  4920.0    0.05       0
  4985.9    0.05       0  4990.6    0.05       0
Bank Sta=4985.9,4990.6
Exp/Cntr=0.3,0.1

Type RM Length L Ch R = 1,2789,262,262,262
BEGIN DESCRIPTION:
Deadman 33 5.0
END DESCRIPTION:
XS GIS Cut Line= 3
      1600112.87      6918724.95      1600205.00      6918488.00
      1600429.99      6918013.03
#Sta/Elev= 30
  4750.3 1608.64  4796.4 1608.04  4801.8 1608.32  4811.4 1607.41  4826.3 1607.18
  4832.9 1606.27  4850.9 1606.81  4905.3 1605.25  4940.5 1605.49  4965.1 1602.63
  4983.1 1602.71  4989.6 1603.17  5001.9 1602.28  5016.3 1602.16  5016.6 1601.66
  5020.7 1601.66  5021.1 1602.16  5064.2 1602.96  5086.9 1603.95  5104.1 1605.35
  5177.9 1605.41  5251.7 1606.89  5297.1 1606.92  5358.6 1607.94  5439.1 1607.14
  5447.1 1608.27  5461.9 1608.51  5479.1 1609.71  5501.9 1608.77  5530.1 1608.41
#Mann=3,-1,0
  4750.3    0.05       0  5016.3    0.03       0  5021.1    0.05       0
Bank Sta=5016.3,5021.1
Exp/Cntr=0.3,0.1

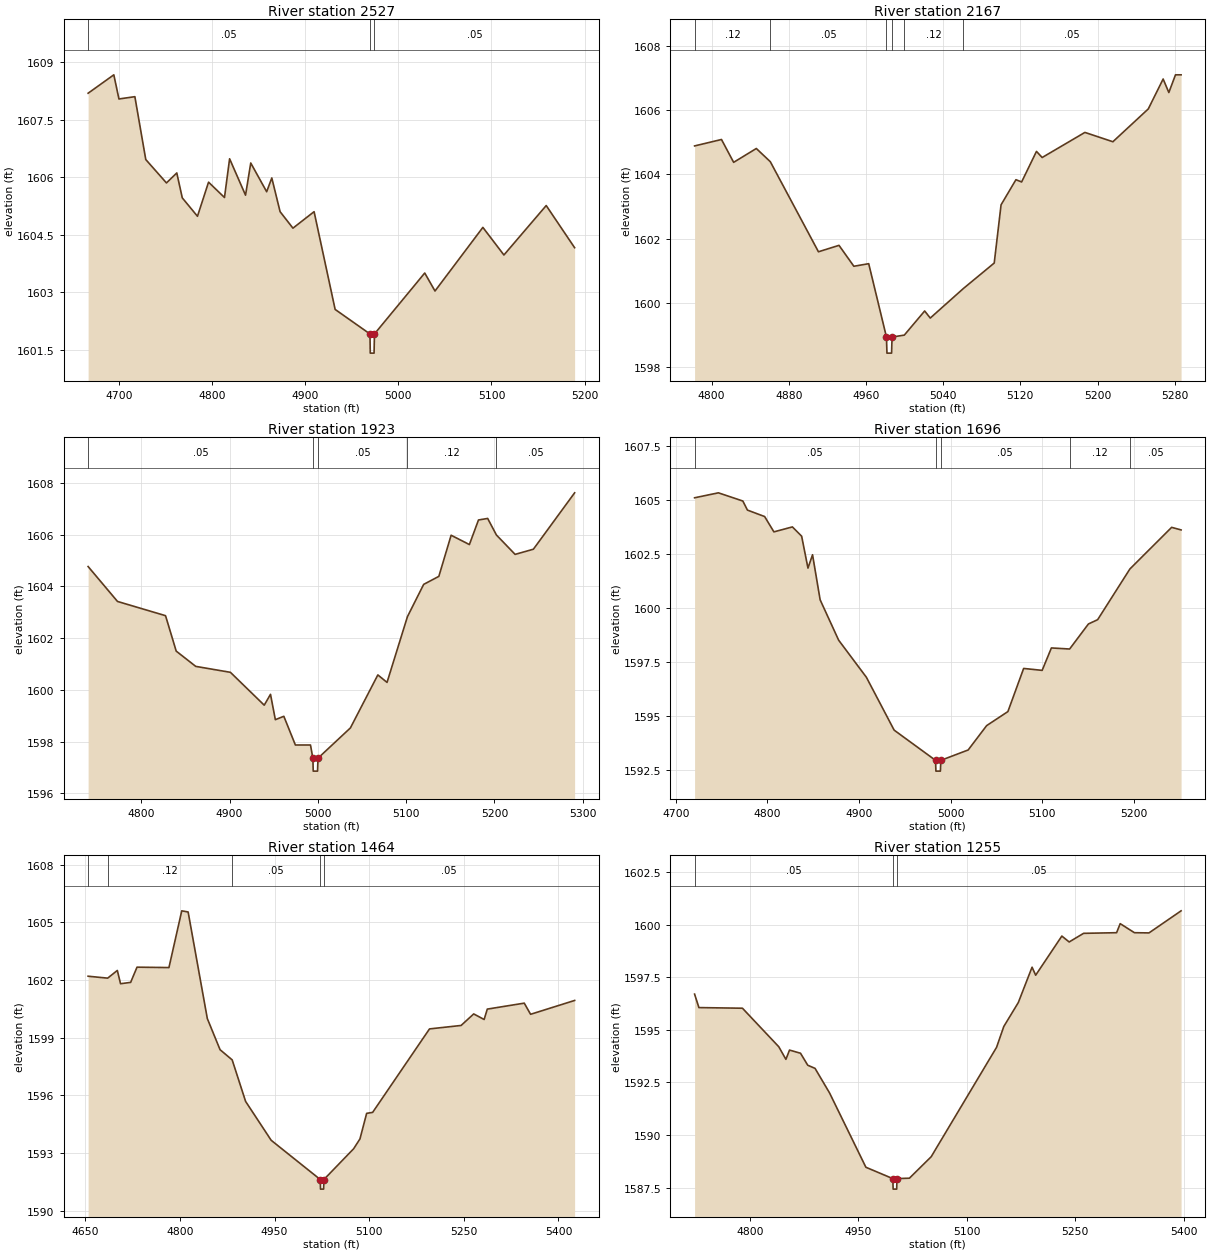
Type RM Length L Ch R = 1,2527,360,360,360
BEGIN DESCRIPTION:
Mapping XS 71cc115c
END DESCRIPTION:
XS GIS Cut Line= 2
      1600109.18      6918786.86      1600580.14      6918561.04
#Sta/Elev= 30
  4667.0 1608.19  4694.6 1608.67  4700.1 1608.04  4717.2 1608.10  4728.9 1606.46
  4751.1 1605.85  4762.2 1606.11  4768.1 1605.46  4784.4 1604.98  4796.3 1605.87
  4813.4 1605.47  4818.9 1606.48  4836.0 1605.53  4841.6 1606.37  4858.7 1605.62
  4864.2 1605.98  4873.1 1605.10  4886.9 1604.67  4909.6 1605.10  4932.2 1602.55
  4969.6 1601.91  4969.9 1601.41  4974.0 1601.41  4974.4 1601.91  5028.4 1603.50
  5039.4 1603.03  5090.8 1604.69  5113.4 1603.97  5158.8 1605.26  5189.3 1604.16
#Mann=3,-1,0
  4667.0    0.05       0  4969.6    0.03       0  4974.4    0.05       0
Bank Sta=4969.6,4974.4
Exp/Cntr=0.3,0.1

Type RM Length L Ch R = 1,2167,244,244,244
BEGIN DESCRIPTION:
Mapping XS 349d3bba
END DESCRIPTION:
XS GIS Cut Line= 2
      1600180.52      6919060.25      1600609.91      6918795.79
#Sta/Elev= 30
  4782.3 1604.88  4810.2 1605.08  4822.8 1604.37  4846.3 1604.80  4860.8 1604.39
  4910.7 1601.59  4932.0 1601.79  4947.4 1601.14  4962.8 1601.22  4981.2 1598.94
  4981.7 1598.44  4986.5 1598.44  4987.0 1598.94  4999.7 1599.00  5020.8 1599.75
  5026.6 1599.53  5061.0 1600.45  5092.9 1601.24  5100.0 1603.05  5115.4 1603.83
  5121.3 1603.76  5136.7 1604.71  5142.6 1604.52  5186.9 1605.30  5215.9 1605.01
  5252.6 1606.03  5268.0 1606.96  5273.9 1606.54  5280.8 1607.09  5286.6 1607.09
#Mann=6,-1,0
  4782.3    0.12       0  4860.8    0.05       0  4981.2    0.07       0
  4987.0    0.05       0  4999.7    0.12       0  5061.0    0.05       0
Bank Sta=4981.2,4987
Exp/Cntr=0.3,0.1

Type RM Length L Ch R = 1,1923,227,227,227
BEGIN DESCRIPTION:
Deadman 33 4.0
END DESCRIPTION:
XS GIS Cut Line= 3
      1600440.23      6919328.01      1600555.00      6919088.00
      1600630.00      6918812.98
#Sta/Elev= 30
  4739.8 1604.77  4773.1 1603.42  4827.5 1602.87  4839.6 1601.50  4861.7 1600.91
  4901.0 1600.68  4939.3 1599.41  4946.4 1599.83  4951.9 1598.85  4961.5 1598.98
  4974.6 1597.87  4991.7 1597.87  4994.4 1597.36  4994.8 1596.86  4999.7 1596.86
  5000.2 1597.36  5036.9 1598.53  5068.0 1600.58  5078.4 1600.29  5101.5 1602.83
  5119.9 1604.08  5137.1 1604.39  5151.0 1605.98  5171.7 1605.62  5182.0 1606.57
  5192.4 1606.63  5202.3 1605.99  5223.5 1605.24  5244.2 1605.44  5290.9 1607.62
#Mann=5,-1,0
  4739.8    0.05       0  4994.4    0.05       0  5000.2    0.05       0
  5101.5    0.12       0  5202.3    0.05       0
Bank Sta=4994.4,5000.2
Exp/Cntr=0.3,0.1

Type RM Length L Ch R = 1,1696,232,232,232
BEGIN DESCRIPTION:
Mapping XS 537837b5
END DESCRIPTION:
XS GIS Cut Line= 2
      1600712.44      6919373.78      1600786.73      6918847.80
#Sta/Elev= 30
  4720.4 1605.11  4746.4 1605.34  4773.1 1604.96  4778.1 1604.54  4796.9 1604.24
  4807.0 1603.53  4827.2 1603.76  4837.3 1603.33  4844.2 1601.85  4849.2 1602.47
  4857.5 1600.38  4877.7 1598.51  4908.0 1596.79  4938.3 1594.34  4983.5 1592.94
  4983.9 1592.44  4988.8 1592.44  4989.3 1592.94  5019.1 1593.42  5039.3 1594.55
  5062.5 1595.20  5079.7 1597.20  5099.9 1597.11  5110.0 1598.15  5129.9 1598.10
  5150.4 1599.26  5160.5 1599.46  5195.7 1601.81  5241.3 1603.74  5251.6 1603.62
#Mann=5,-1,0
  4720.4    0.05       0  4983.5    0.05       0  4989.3    0.05       0
  5129.9    0.12       0  5195.7    0.05       0
Bank Sta=4983.5,4989.3
Exp/Cntr=0.3,0.1

Type RM Length L Ch R = 1,1464,209,209,209
BEGIN DESCRIPTION:
Deadman 33 3.0
END DESCRIPTION:
XS GIS Cut Line= 3
      1600902.16      6919524.59      1600955.00      6919188.00
      1600932.62      6918758.30
#Sta/Elev= 30
  4654.6 1602.20  4685.6 1602.10  4700.9 1602.50  4706.0 1601.81  4722.0 1601.88
  4732.1 1602.67  4782.7 1602.65  4803.0 1605.60  4813.1 1605.54  4843.5 1600.00
  4863.7 1598.38  4882.9 1597.85  4904.2 1595.69  4944.7 1593.67  5022.5 1591.63
  5022.9 1591.13  5027.8 1591.13  5028.3 1591.63  5075.4 1593.23  5085.4 1593.74
  5096.0 1595.07  5105.5 1595.12  5195.6 1599.46  5245.7 1599.64  5265.7 1600.24
  5282.2 1599.95  5287.2 1600.49  5345.8 1600.80  5355.8 1600.22  5425.6 1600.94
#Mann=5,-1,0
  4654.6    0.05       0  4685.6    0.12       0  4882.9    0.05       0
  5022.5    0.03       0  5028.3    0.05       0
Bank Sta=5022.5,5028.3
Exp/Cntr=0.3,0.1

Type RM Length L Ch R = 1,1255,273,273,273
BEGIN DESCRIPTION:
Mapping XS 8ff0a255
END DESCRIPTION:
XS GIS Cut Line= 2
      1601171.58      6919413.93      1601112.15      6918743.76
#Sta/Elev= 30
  4723.7 1596.70  4729.7 1596.06  4789.9 1596.03  4840.1 1594.20  4850.0 1593.60
  4855.0 1594.04  4870.2 1593.89  4880.2 1593.32  4890.3 1593.17  4910.4 1592.00
  4960.6 1588.47  4997.8 1587.93  4998.3 1587.43  5003.2 1587.43  5003.6 1587.93
  5020.8 1587.95  5050.9 1588.97  5141.3 1594.17  5151.3 1595.16  5171.4 1596.30
  5190.4 1597.98  5195.4 1597.60  5231.6 1599.46  5241.7 1599.18  5261.7 1599.59
  5307.3 1599.62  5312.3 1600.05  5332.0 1599.62  5352.1 1599.61  5396.5 1600.66
#Mann=3,-1,0
  4723.7    0.05       0  4997.8    0.03       0  5003.6    0.05       0
Bank Sta=4997.8,5003.6
Exp/Cntr=0.3,0.1

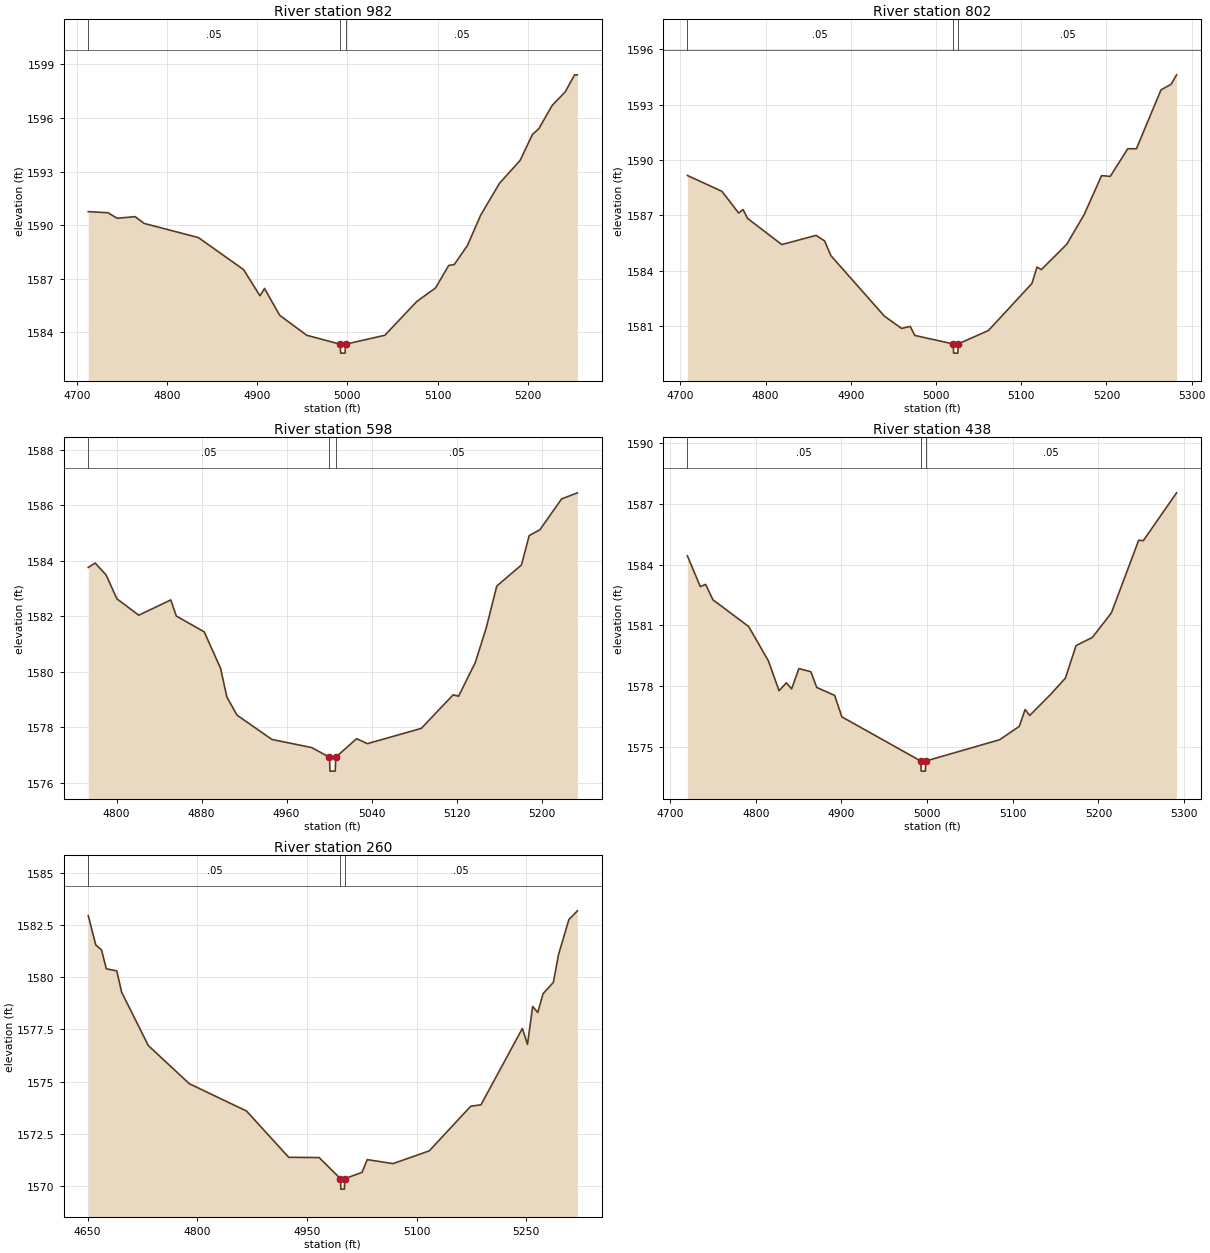
Type RM Length L Ch R = 1,982,180,180,180
BEGIN DESCRIPTION:
Deadman 33 2.0
END DESCRIPTION:
XS GIS Cut Line= 3
      1601419.81      6919379.92      1601405.00      6919088.00
      1601255.00      6918888.00
#Sta/Elev= 30
  4712.8 1590.76  4734.7 1590.70  4744.8 1590.39  4764.8 1590.48  4774.8 1590.10
  4834.9 1589.31  4884.9 1587.52  4903.2 1586.05  4908.2 1586.46  4925.0 1584.96
  4955.0 1583.84  4992.1 1583.34  4992.6 1582.84  4997.5 1582.84  4998.0 1583.34
  5041.6 1583.84  5077.0 1585.73  5097.8 1586.49  5112.4 1587.75  5118.6 1587.80
  5133.2 1588.87  5147.8 1590.56  5168.6 1592.34  5191.6 1593.63  5205.1 1595.07
  5212.4 1595.41  5227.0 1596.70  5241.6 1597.47  5252.0 1598.42  5255.1 1598.42
#Mann=3,-1,0
  4712.8    0.05       0  4992.1    0.05       0  4998.0    0.05       0
Bank Sta=4992.1,4998
Exp/Cntr=0.3,0.1

Type RM Length L Ch R = 1,802,204,204,204
BEGIN DESCRIPTION:
Mapping XS a116c436
END DESCRIPTION:
XS GIS Cut Line= 3
      1601563.86      6919378.30      1601589.12      6919112.28
      1601526.97      6918811.85
#Sta/Elev= 30
  4708.3 1589.16  4748.8 1588.30  4768.5 1587.12  4773.6 1587.31  4778.9 1586.83
  4819.1 1585.41  4859.3 1585.91  4869.3 1585.61  4876.7 1584.81  4939.6 1581.52
  4959.7 1580.86  4969.8 1580.97  4975.1 1580.48  5020.2 1580.02  5020.7 1579.52
  5025.6 1579.52  5026.1 1580.02  5061.6 1580.75  5112.6 1583.30  5118.5 1584.19
  5123.6 1584.05  5153.5 1585.43  5173.9 1587.04  5194.3 1589.15  5204.5 1589.11
  5225.0 1590.61  5235.2 1590.61  5264.0 1593.80  5276.0 1594.11  5282.3 1594.62
#Mann=3,-1,0
  4708.3    0.05       0  5020.2    0.03       0  5026.1    0.05       0
Bank Sta=5020.2,5026.1
Exp/Cntr=0.3,0.1

Type RM Length L Ch R = 1,598,160,160,160
BEGIN DESCRIPTION:
Mapping XS a8b44502
END DESCRIPTION:
XS GIS Cut Line= 3
      1601731.26      6919334.31      1601781.88      6919118.03
      1601740.45      6918883.28
#Sta/Elev= 30
  4773.3 1583.76  4779.8 1583.92  4790.1 1583.49  4800.3 1582.63  4820.9 1582.04
  4851.0 1582.59  4856.2 1582.01  4882.5 1581.44  4897.9 1580.12  4903.8 1579.09
  4913.3 1578.44  4946.3 1577.56  4983.6 1577.27  5000.4 1576.92  5000.9 1576.42
  5005.8 1576.42  5006.3 1576.92  5025.9 1577.59  5036.1 1577.41  5086.8 1577.96
  5116.8 1579.17  5121.9 1579.12  5137.6 1580.33  5147.8 1581.56  5157.9 1583.09
  5181.1 1583.85  5188.4 1584.91  5198.5 1585.12  5218.9 1586.23  5233.8 1586.45
#Mann=3,-1,0
  4773.3    0.05       0  5000.4    0.03       0  5006.3    0.05       0
Bank Sta=5000.4,5006.3
Exp/Cntr=0.3,0.1

Type RM Length L Ch R = 1,438,178,178,178
BEGIN DESCRIPTION:
Mapping XS 2da0ab81
END DESCRIPTION:
XS GIS Cut Line= 3
      1601770.38      6919364.25      1601933.76      6919141.04
      1601825.61      6918867.23
#Sta/Elev= 30
  4720.2 1584.43  4735.3 1582.91  4741.5 1583.02  4750.0 1582.26  4791.7 1580.94
  4814.7 1579.25  4827.2 1577.77  4835.7 1578.16  4841.9 1577.86  4850.3 1578.86
  4864.3 1578.71  4871.2 1577.93  4892.1 1577.54  4900.5 1576.48  4992.6 1574.30
  4993.1 1573.80  4998.0 1573.80  4998.5 1574.30  5084.7 1575.35  5107.6 1576.01
  5114.4 1576.84  5119.8 1576.55  5144.2 1577.59  5161.4 1578.39  5173.9 1580.00
  5192.9 1580.40  5215.1 1581.61  5247.0 1585.20  5252.4 1585.18  5291.2 1587.54
#Mann=3,-1,0
  4720.2    0.05       0  4992.6    0.03       0  4998.5    0.05       0
Bank Sta=4992.6,4998.5
Exp/Cntr=0.3,0.1

Type RM Length L Ch R = 1,260,0,0,0
BEGIN DESCRIPTION:
Deadman 33 1.0
END DESCRIPTION:
XS GIS Cut Line= 3
      1601839.41      6919357.35      1602110.94      6919138.74
      1601883.17      6918913.26
#Sta/Elev= 30
  4650.8 1582.94  4661.1 1581.54  4669.0 1581.30  4675.5 1580.40  4689.8 1580.30
  4696.5 1579.28  4733.0 1576.73  4789.0 1574.91  4867.4 1573.60  4925.0 1571.39
  4966.6 1571.38  4995.8 1570.37  4996.3 1569.87  5001.2 1569.87  5001.7 1570.37
  5025.3 1570.67  5032.4 1571.28  5067.7 1571.09  5117.3 1571.70  5173.9 1573.83
  5188.0 1573.90  5244.6 1577.55  5251.6 1576.79  5258.7 1578.60  5265.7 1578.31
  5272.9 1579.21  5287.0 1579.75  5294.0 1581.07  5308.2 1582.75  5319.9 1583.17
#Mann=3,-1,0
  4650.8    0.05       0  4995.8    0.05       0  5001.7    0.05       0
Bank Sta=4995.8,5001.7
Exp/Cntr=0.3,0.1

Chan Stop Cuts=-1