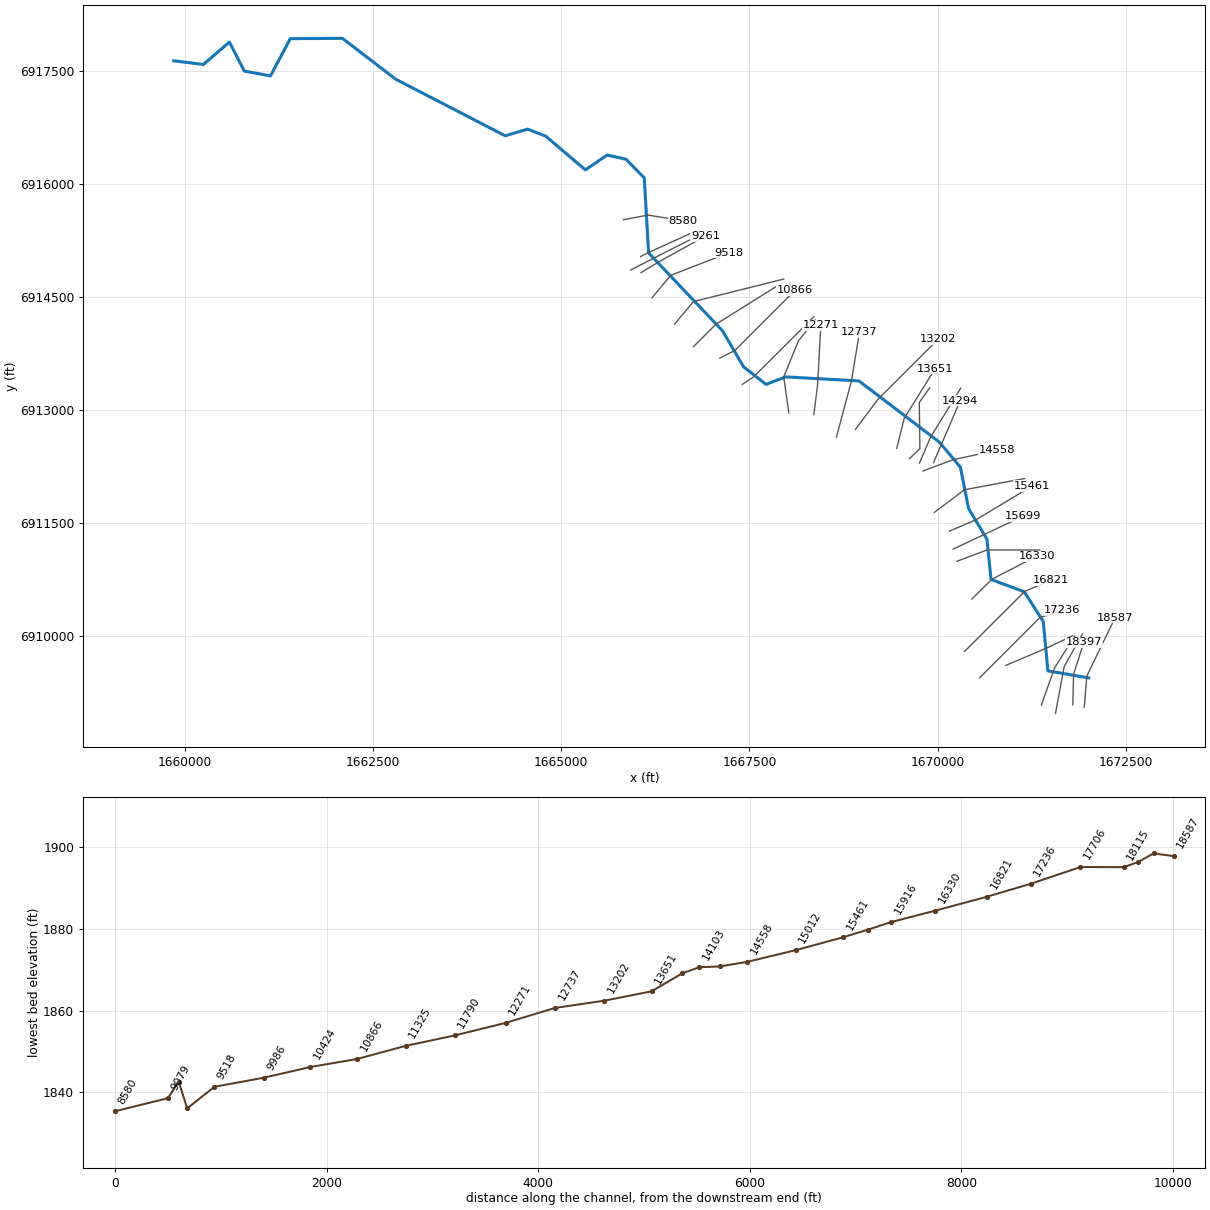
--- Deadman 34.prj (project) ---

Proj Title=Deadman 34 Base Level Engineering
Current Plan=p01
Default Exp/Contr=0.3,0.1
English Units
Geom File=g01
Flow File=f01
Plan File=p01
BEGIN DESCRIPTION:
Deadman 34
END DESCRIPTION:

--- Deadman 34.p01 (plan) ---

Plan Title=Multiple Run
Short Identifier=Multiple
Geom File=g01
Flow File=f01
Subcritical Flow
K Sum by GR= 0
Std Step Tol= 0.01
Critical Tol= 0.01
Num of Std Step Trials= 20
Max Error Tol= 0.3
Flow Tol Ratio= 0.001
Split Flow NTrial= 30
Split Flow Tol= 0.02
Split Flow Ratio= 0.02
Log Output Level= 0
Friction Slope Method= 1
Unsteady Friction Slope Method= 2
Unsteady Bridges Friction Slope Method= 1
Parabolic Critical Depth
Global Vel Dist=  1 , 1 , 1
Global Log Level= 0
CheckData=True
Encroach Param= -1, 0, 0, 0
BEGIN DESCRIPTION:
Multiple Run
END DESCRIPTION:

--- Deadman 34.f01 (steady flow) ---

Flow Title=Multiple
Number of Profiles=7
Profile Names=10-year,25-year,50-year,1pct_min,100-year,1pct_plu,500-year
River Rch & RM= Deadman 34,Reach-1,18587
     290     404     498     306     611    1220     931
River Rch & RM= Deadman 34,Reach-1,14294
     426     607     760     473     944    1883    1477
River Rch & RM= Deadman 34,Reach-1,13202
     529     760     957     599    1195    2385    1889
River Rch & RM= Deadman 34,Reach-1,7225
     574     826    1041     652    1301    2597    2060
Boundary for River Rch & Prof#=Deadman 34,Reach-1,1
Up Type=0
Dn Type=3
Dn Slope=0.009
Boundary for River Rch & Prof#=Deadman 34,Reach-1,2
Up Type=0
Dn Type=3
Dn Slope=0.009
Boundary for River Rch & Prof#=Deadman 34,Reach-1,3
Up Type=0
Dn Type=3
Dn Slope=0.009
Boundary for River Rch & Prof#=Deadman 34,Reach-1,4
Up Type=0
Dn Type=3
Dn Slope=0.009
Boundary for River Rch & Prof#=Deadman 34,Reach-1,5
Up Type=0
Dn Type=3
Dn Slope=0.009
Boundary for River Rch & Prof#=Deadman 34,Reach-1,6
Up Type=0
Dn Type=3
Dn Slope=0.009
Boundary for River Rch & Prof#=Deadman 34,Reach-1,7
Up Type=0
Dn Type=3
Dn Slope=0.009

--- Deadman 34.g01 (geometry) ---

Geom Title=Existing Conditions

River Reach=Deadman 34,Reach-1
Reach XY= 30
      1672005.00      6909438.00      1671462.72      6909531.50
      1671401.24      6910186.44      1671149.41      6910582.39
      1670707.93      6910745.97      1670652.74      6911282.06
      1670408.82      6911689.58      1670301.39      6912236.50
      1670021.52      6912571.31      1668953.54      6913384.46
      1667979.92      6913438.20      1667720.39      6913338.08
      1667421.70      6913571.51      1667141.37      6914051.21
      1666160.47      6915085.55      1666102.94      6916082.15
      1665861.19      6916330.18      1665610.97      6916386.07
      1665321.00      6916188.77      1664796.65      6916634.81
      1664554.92      6916730.70      1664256.55      6916641.75
      1662802.70      6917393.83      1662094.57      6917936.95
      1661402.55      6917932.54      1661139.85      6917438.38
      1660791.78      6917501.62      1660594.69      6917887.14
      1660249.12      6917589.96      1659855.00      6917638.00

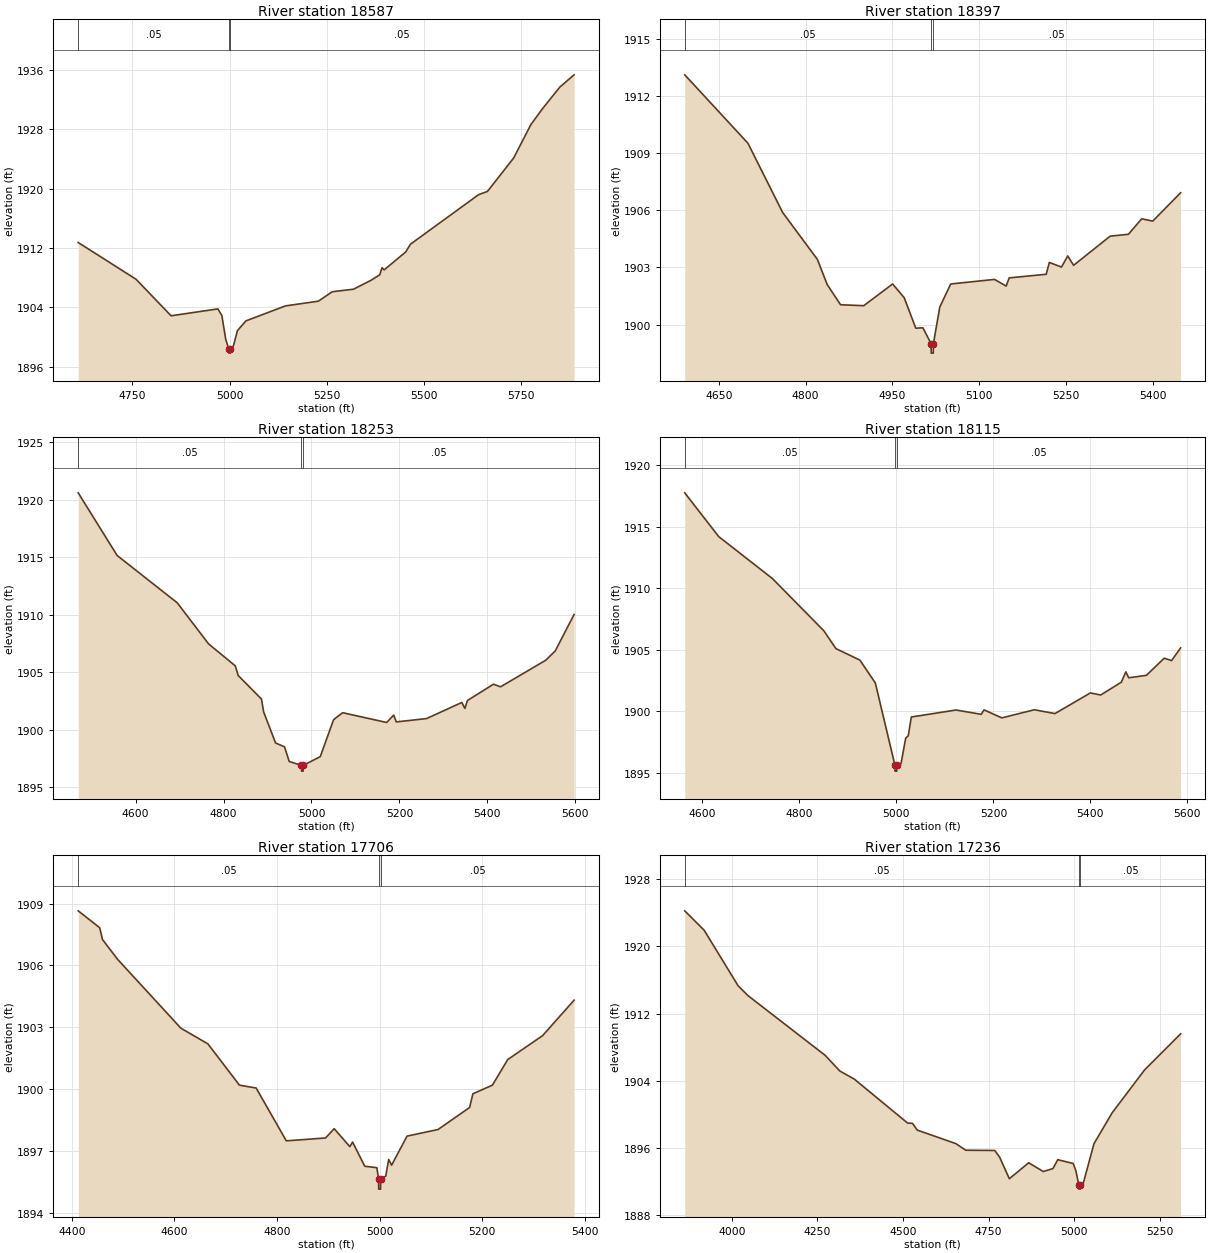
Type RM Length L Ch R = 1,18587,190,190,190
BEGIN DESCRIPTION:
Deadman 34 37.0
END DESCRIPTION:
XS GIS Cut Line= 3
      1671945.75      6909049.89      1671980.00      6909463.00
      1672355.00      6910238.01
#Sta/Elev= 30
  4610.8 1912.74  4759.4 1907.80  4849.7 1902.87  4970.1 1903.80  4980.2 1902.92
  4990.2 1899.73  4998.2 1898.34  4998.5 1897.84  5002.0 1897.84  5002.2 1898.34
  5010.3 1898.86  5020.3 1900.86  5042.0 1902.18  5143.8 1904.20  5228.6 1904.84
  5264.2 1906.11  5319.0 1906.45  5364.2 1907.66  5386.4 1908.39  5392.3 1909.35
  5397.9 1909.06  5453.0 1911.46  5465.6 1912.52  5640.8 1919.19  5663.4 1919.62
  5730.8 1924.12  5775.2 1928.63  5804.5 1930.73  5849.6 1933.68  5886.3 1935.33
#Mann=3,-1,0
  4610.8    0.05       0  4998.2    0.03       0  5002.2    0.05       0
Bank Sta=4998.2,5002.2
Exp/Cntr=0.3,0.1

Type RM Length L Ch R = 1,18397,144,144,144
BEGIN DESCRIPTION:
Mapping XS ccd478b5
END DESCRIPTION:
XS GIS Cut Line= 3
      1671793.72      6909078.79      1671804.14      6909490.24
      1671941.87      6909913.82
#Sta/Elev= 30
  4591.0 1913.11  4700.2 1909.52  4760.3 1905.88  4820.3 1903.42  4837.2 1902.10
  4860.3 1901.04  4900.3 1900.99  4950.3 1902.13  4970.3 1901.41  4990.3 1899.81
  5002.6 1899.83  5016.7 1899.00  5017.0 1898.50  5020.5 1898.50  5020.8 1899.00
  5031.8 1900.92  5050.7 1902.13  5126.4 1902.37  5146.5 1902.02  5151.8 1902.45
  5215.7 1902.64  5221.1 1903.26  5242.1 1903.02  5252.9 1903.60  5263.1 1903.11
  5326.2 1904.64  5357.8 1904.74  5380.7 1905.55  5399.8 1905.43  5448.0 1906.92
#Mann=3,-1,0
  4591.0    0.05       0  5016.7    0.03       0  5020.8    0.05       0
Bank Sta=5016.7,5020.8
Exp/Cntr=0.3,0.1

Type RM Length L Ch R = 1,18253,138,138,138
BEGIN DESCRIPTION:
Mapping XS c25ad028
END DESCRIPTION:
XS GIS Cut Line= 3
      1671563.80      6908966.51      1671678.39      6909588.06
      1671920.73      6910020.80
#Sta/Elev= 30
  4469.4 1920.61  4558.0 1915.16  4694.6 1911.05  4765.8 1907.48  4826.8 1905.56
  4833.2 1904.73  4886.2 1902.68  4891.3 1901.55  4918.3 1898.86  4938.7 1898.52
  4949.4 1897.25  4977.3 1896.91  4977.5 1896.41  4981.1 1896.41  4981.4 1896.91
  5020.0 1897.67  5050.3 1900.88  5070.9 1901.49  5171.0 1900.64  5187.0 1901.28
  5193.0 1900.69  5261.8 1900.98  5342.0 1902.38  5349.0 1901.87  5354.8 1902.55
  5414.1 1903.97  5430.1 1903.74  5532.8 1906.05  5554.5 1906.86  5597.4 1910.03
#Mann=3,-1,0
  4469.4    0.05       0  4977.3    0.03       0  4981.4    0.05       0
Bank Sta=4977.3,4981.4
Exp/Cntr=0.3,0.1

Type RM Length L Ch R = 1,18115,409,409,409
BEGIN DESCRIPTION:
Mapping XS e524a7ff
END DESCRIPTION:
XS GIS Cut Line= 3
      1671376.31      6909077.64      1671549.92      6909567.22
      1671816.84      6909993.61
#Sta/Elev= 30
  4563.6 1917.76  4633.7 1914.20  4744.4 1910.79  4850.5 1906.54  4875.4 1905.09
  4924.7 1904.16  4956.6 1902.30  4996.9 1895.63  4997.2 1895.13  5000.8 1895.13
  5001.0 1895.63  5009.6 1895.74  5019.2 1897.81  5024.5 1898.01  5030.8 1899.53
  5123.1 1900.10  5174.9 1899.75  5180.8 1900.11  5217.4 1899.46  5284.5 1900.12
  5327.0 1899.81  5400.1 1901.49  5421.3 1901.32  5463.8 1902.36  5473.2 1903.20
  5479.1 1902.72  5515.6 1902.92  5552.2 1904.31  5567.5 1904.12  5586.1 1905.15
#Mann=3,-1,0
  4563.6    0.05       0  4996.9    0.03       0  5001.0    0.05       0
Bank Sta=4996.9,5001
Exp/Cntr=0.3,0.1

Type RM Length L Ch R = 1,17706,470,470,470
BEGIN DESCRIPTION:
Deadman 34 36.0
END DESCRIPTION:
XS GIS Cut Line= 3
      1670905.68      6909604.82      1671455.00      6909838.00
      1671788.52      6909998.06
#Sta/Elev= 30
  4412.5 1908.65  4454.4 1907.83  4459.8 1907.26  4488.9 1906.31  4612.7 1902.96
  4665.4 1902.20  4726.8 1900.20  4759.4 1900.06  4818.2 1897.50  4894.6 1897.64
  4911.5 1898.09  4942.0 1897.22  4947.4 1897.44  4971.1 1896.27  4994.7 1896.20
  4998.1 1895.66  4998.3 1895.16  5001.9 1895.16  5002.2 1895.66  5012.0 1895.79
  5017.8 1896.60  5023.4 1896.32  5053.6 1897.73  5114.0 1898.05  5175.6 1899.12
  5181.9 1899.78  5220.0 1900.20  5249.8 1901.44  5317.8 1902.60  5379.2 1904.32
#Mann=3,-1,0
  4412.5    0.05       0  4998.1    0.03       0  5002.2    0.05       0
Bank Sta=4998.1,5002.2
Exp/Cntr=0.3,0.1

Type RM Length L Ch R = 1,17236,415,415,415
BEGIN DESCRIPTION:
Deadman 34 35.0
END DESCRIPTION:
XS GIS Cut Line= 3
      1670554.97      6909437.97      1671355.00      6910238.00
      1671654.97      6910337.99
#Sta/Elev= 30
  3862.9 1924.25  3919.5 1921.94  4018.5 1915.33  4046.8 1914.16  4273.1 1907.01
  4315.5 1905.15  4357.9 1904.18  4513.5 1898.94  4527.6 1898.91  4541.8 1898.10
  4654.9 1896.48  4683.2 1895.70  4768.0 1895.67  4782.2 1894.87  4810.5 1892.30
  4867.0 1894.20  4909.5 1893.16  4937.7 1893.51  4951.9 1894.57  4996.9 1894.12
  5004.8 1893.24  5013.3 1891.56  5013.6 1891.06  5017.2 1891.06  5017.5 1891.56
  5025.9 1891.70  5057.6 1896.48  5110.3 1900.14  5205.1 1905.27  5310.5 1909.58
#Mann=3,-1,0
  3862.9    0.05       0  5013.3    0.03       0  5017.5    0.05       0
Bank Sta=5013.3,5017.5
Exp/Cntr=0.3,0.1

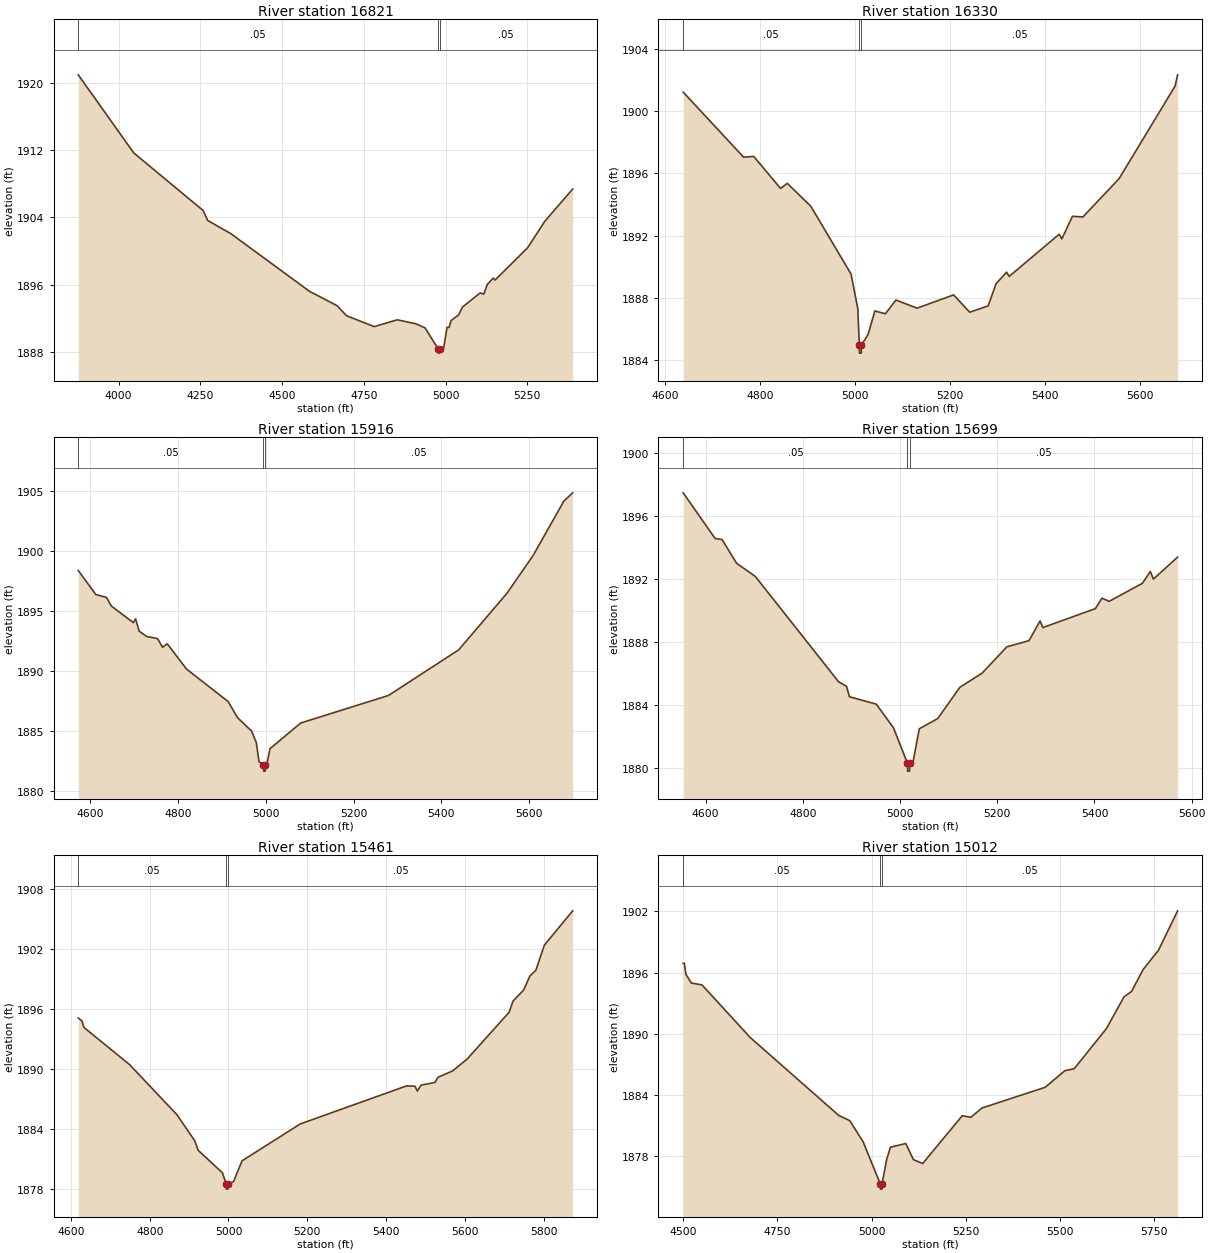
Type RM Length L Ch R = 1,16821,491,491,491
BEGIN DESCRIPTION:
Deadman 34 34.0
END DESCRIPTION:
XS GIS Cut Line= 3
      1670355.03      6909788.03      1671155.00      6910588.00
      1671504.99      6910737.99
#Sta/Elev= 30
  3876.6 1920.95  4046.3 1911.67  4258.4 1904.83  4272.5 1903.64  4343.2 1902.08
  4583.7 1895.23  4668.5 1893.51  4696.8 1892.33  4781.7 1891.03  4852.4 1891.84
  4908.9 1891.37  4937.2 1890.88  4977.5 1888.38  4977.8 1887.88  4981.5 1887.88
  4981.8 1888.38  4993.8 1888.41  5004.4 1890.94  5010.6 1890.94  5017.0 1891.75
  5040.6 1892.45  5051.4 1893.35  5105.8 1895.03  5116.7 1894.89  5127.6 1896.04
  5145.7 1896.80  5151.2 1896.56  5250.9 1900.40  5303.5 1903.55  5388.7 1907.38
#Mann=3,-1,0
  3876.6    0.05       0  4977.5    0.03       0  4981.8    0.05       0
Bank Sta=4977.5,4981.8
Exp/Cntr=0.3,0.1

Type RM Length L Ch R = 1,16330,414,414,414
BEGIN DESCRIPTION:
Deadman 34 33.0
END DESCRIPTION:
XS GIS Cut Line= 3
      1670455.00      6910488.00      1670720.80      6910750.66
      1671314.59      6911055.37
#Sta/Elev= 30
  4638.7 1901.22  4765.9 1897.04  4787.2 1897.09  4843.8 1895.03  4857.9 1895.36
  4907.4 1893.89  4992.2 1889.53  5006.4 1887.31  5009.6 1884.95  5009.9 1884.45
  5013.7 1884.45  5014.0 1884.95  5028.3 1885.67  5042.3 1887.16  5064.5 1886.98
  5086.7 1887.86  5131.1 1887.34  5208.2 1888.19  5242.0 1887.08  5280.8 1887.48
  5297.4 1888.90  5319.6 1889.65  5325.2 1889.38  5430.5 1892.09  5436.1 1891.79
  5458.3 1893.24  5480.5 1893.20  5556.6 1895.66  5674.6 1901.61  5679.8 1902.33
#Mann=3,-1,0
  4638.7    0.05       0  5009.6    0.03       0  5014.0    0.05       0
Bank Sta=5009.6,5014
Exp/Cntr=0.3,0.1

Type RM Length L Ch R = 1,15916,217,217,217
BEGIN DESCRIPTION:
Deadman 34 32.0
END DESCRIPTION:
XS GIS Cut Line= 3
      1670254.98      6910987.99      1670655.00      6911138.00
      1671354.98      6911138.00
#Sta/Elev= 30
  4572.3 1898.36  4612.4 1896.36  4636.4 1896.13  4648.0 1895.40  4697.8 1894.03
  4703.1 1894.34  4711.2 1893.31  4728.1 1892.88  4753.0 1892.70  4764.6 1891.98
  4775.2 1892.27  4818.8 1890.18  4914.1 1887.46  4935.4 1886.13  4967.5 1885.01
  4978.2 1884.06  4984.4 1882.47  4994.6 1882.18  4994.9 1881.68  4998.7 1881.68
  4999.0 1882.18  5002.0 1882.18  5009.5 1883.55  5079.5 1885.68  5279.5 1887.97
  5439.5 1891.76  5549.5 1896.46  5609.5 1899.62  5679.5 1904.14  5699.5 1904.82
#Mann=3,-1,0
  4572.3    0.05       0  4994.6    0.03       0  4999.0    0.05       0
Bank Sta=4994.6,4999
Exp/Cntr=0.3,0.1

Type RM Length L Ch R = 1,15699,238,238,238
BEGIN DESCRIPTION:
Mapping XS 4ab58fee
END DESCRIPTION:
XS GIS Cut Line= 2
      1670205.56      6911149.77      1671125.71      6911583.85
#Sta/Elev= 30
  4553.7 1897.45  4619.4 1894.56  4633.8 1894.49  4663.6 1892.99  4702.1 1892.16
  4873.7 1885.48  4889.9 1885.20  4895.8 1884.54  4951.1 1884.07  4986.5 1882.57
  5015.2 1880.33  5015.5 1879.83  5019.4 1879.83  5019.7 1880.33  5026.5 1880.38
  5039.6 1882.51  5077.6 1883.16  5123.1 1885.14  5168.7 1886.03  5219.8 1887.70
  5265.3 1888.09  5288.1 1889.34  5293.9 1888.92  5402.0 1890.12  5415.5 1890.78
  5430.3 1890.58  5498.6 1891.72  5515.0 1892.47  5521.4 1891.99  5571.1 1893.38
#Mann=3,-1,0
  4553.7    0.05       0  5015.2    0.03       0  5019.7    0.05       0
Bank Sta=5015.2,5019.7
Exp/Cntr=0.3,0.1

Type RM Length L Ch R = 1,15461,449,449,449
BEGIN DESCRIPTION:
Deadman 34 31.0
END DESCRIPTION:
XS GIS Cut Line= 3
      1670154.97      6911387.99      1670505.00      6911538.00
      1671255.03      6911988.02
#Sta/Elev= 30
  4618.5 1895.06  4627.6 1894.79  4633.0 1894.12  4749.1 1890.39  4868.8 1885.40
  4914.1 1882.79  4923.2 1881.82  4984.8 1879.56  4994.3 1878.44  4994.7 1877.94
  4998.6 1877.94  4998.9 1878.44  5012.9 1878.70  5034.3 1880.77  5182.0 1884.46
  5452.2 1888.27  5473.6 1888.24  5479.4 1887.76  5489.1 1888.35  5524.1 1888.61
  5531.9 1889.13  5568.8 1889.76  5605.7 1890.94  5712.6 1895.64  5722.4 1896.75
  5749.6 1897.87  5765.1 1899.25  5780.7 1899.86  5802.0 1902.35  5874.0 1905.79
#Mann=3,-1,0
  4618.5    0.05       0  4994.3    0.03       0  4998.9    0.05       0
Bank Sta=4994.3,4998.9
Exp/Cntr=0.3,0.1

Type RM Length L Ch R = 1,15012,454,454,454
BEGIN DESCRIPTION:
Deadman 34 30.0
END DESCRIPTION:
XS GIS Cut Line= 3
      1669955.03      6911638.02      1670355.00      6911938.00
      1671154.99      6912088.00
#Sta/Elev= 30
  4499.5 1896.91  4502.6 1896.91  4506.8 1895.83  4521.3 1894.97  4549.5 1894.79
  4677.6 1889.64  4913.0 1882.00  4942.2 1881.49  4977.6 1879.42  5023.5 1875.28
  5023.8 1874.78  5027.8 1874.78  5028.1 1875.28  5040.2 1877.69  5050.3 1878.89
  5091.0 1879.25  5111.4 1877.67  5136.0 1877.29  5241.1 1881.97  5264.0 1881.82
  5293.7 1882.73  5461.5 1884.76  5514.1 1886.39  5538.7 1886.58  5624.3 1890.51
  5671.0 1893.62  5691.3 1894.16  5721.8 1896.30  5762.5 1898.18  5813.4 1902.05
#Mann=3,-1,0
  4499.5    0.05       0  5023.5    0.03       0  5028.1    0.05       0
Bank Sta=5023.5,5028.1
Exp/Cntr=0.3,0.1

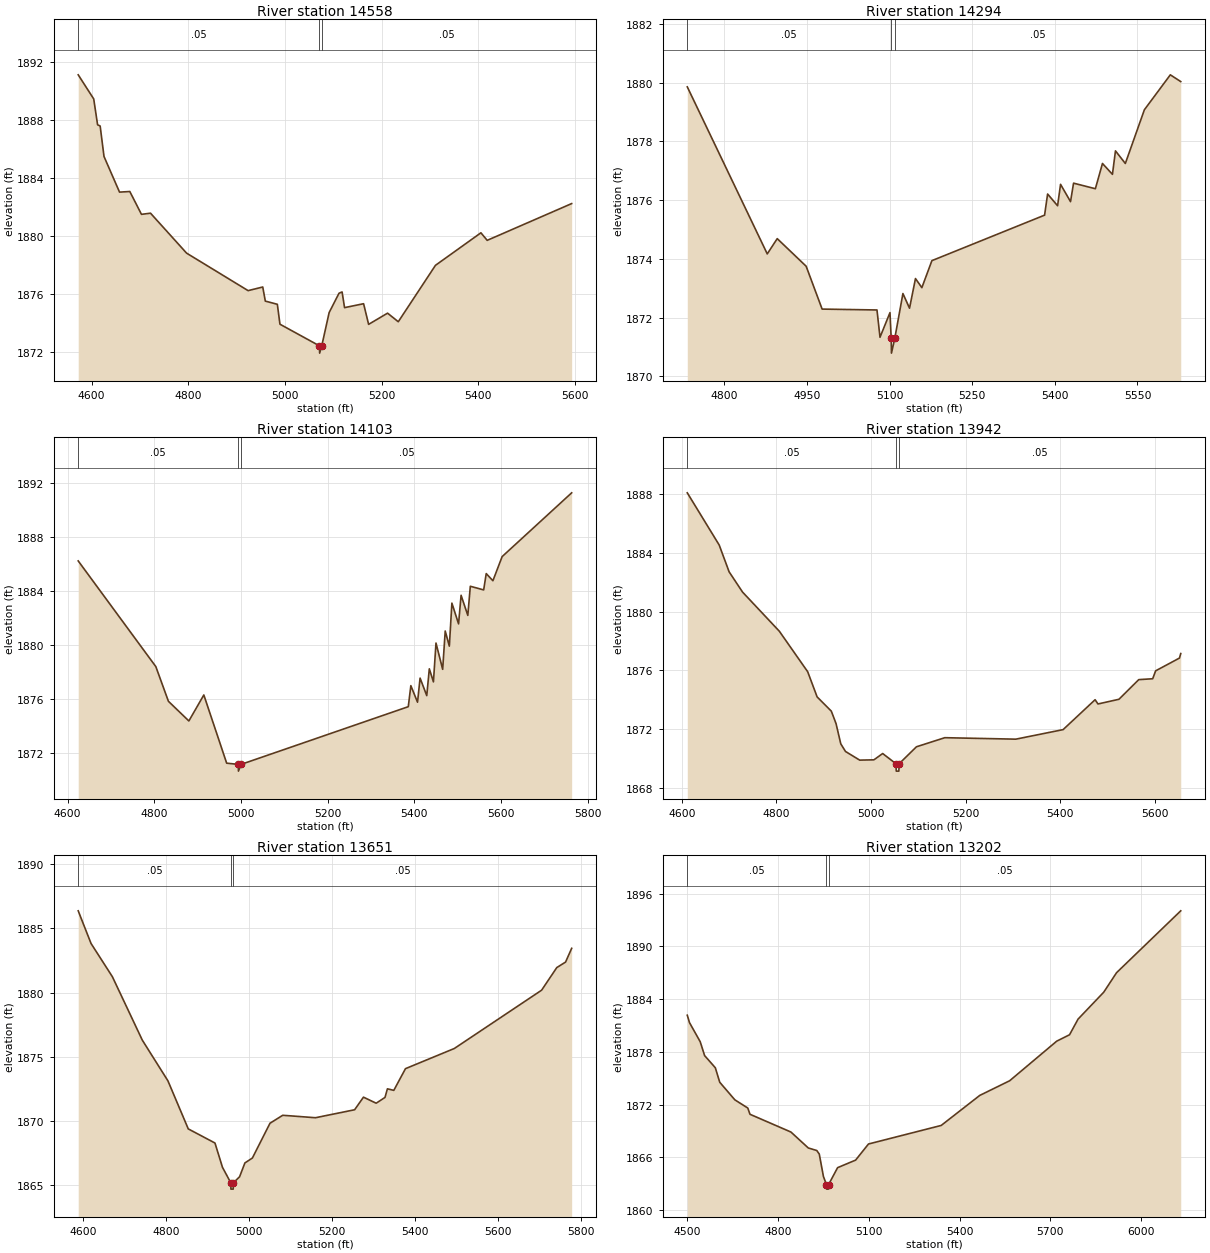
Type RM Length L Ch R = 1,14558,264,264,264
BEGIN DESCRIPTION:
Deadman 34 29.0
END DESCRIPTION:
XS GIS Cut Line= 3
      1669804.96      6912187.98      1670205.00      6912338.00
      1670785.95      6912461.61
#Sta/Elev= 30
  4572.3 1891.09  4604.4 1889.43  4612.4 1887.65  4617.7 1887.57  4625.7 1885.47
  4657.8 1883.02  4679.1 1883.06  4703.2 1881.49  4721.9 1881.57  4796.6 1878.82
  4923.9 1876.24  4954.2 1876.49  4959.5 1875.52  4984.4 1875.30  4989.8 1873.93
  5071.6 1872.44  5071.9 1871.94  5076.3 1872.44  5091.6 1874.73  5112.0 1876.06
  5118.4 1876.15  5123.5 1875.07  5162.9 1875.34  5173.3 1873.92  5212.5 1874.69
  5234.7 1874.10  5311.6 1877.98  5405.7 1880.22  5418.7 1879.70  5593.5 1882.23
#Mann=3,-1,0
  4572.3    0.05       0  5071.6    0.03       0  5076.3    0.05       0
Bank Sta=5071.6,5076.3
Exp/Cntr=0.3,0.1

Type RM Length L Ch R = 1,14294,191,191,191
BEGIN DESCRIPTION:
Mapping XS 12111234
END DESCRIPTION:
XS GIS Cut Line= 2
      1669943.66      6912297.34      1670297.44      6913120.42
#Sta/Elev= 30
  4732.7 1879.86  4877.9 1874.17  4896.0 1874.69  4948.5 1873.75  4977.5 1872.29
  5077.1 1872.26  5082.6 1871.33  5100.7 1872.17  5102.9 1871.29  5103.4 1870.79
  5109.4 1871.29  5124.2 1872.82  5136.2 1872.32  5147.0 1873.33  5158.6 1873.02
  5176.8 1873.94  5381.4 1875.49  5386.9 1876.21  5405.0 1875.81  5410.4 1876.54
  5428.5 1875.95  5434.0 1876.58  5473.6 1876.39  5486.5 1877.25  5504.6 1876.88
  5510.1 1877.68  5528.0 1877.25  5562.6 1879.08  5609.7 1880.27  5628.6 1880.04
#Mann=3,-1,0
  4732.7    0.05       0  5102.9    0.05       0  5109.4    0.05       0
Bank Sta=5102.9,5109.4
Exp/Cntr=0.3,0.1

Type RM Length L Ch R = 1,14103,161,161,161
BEGIN DESCRIPTION:
Deadman 34 28.0
END DESCRIPTION:
XS GIS Cut Line= 3
      1669757.67      6912293.00      1669905.00      6912638.00
      1670305.02      6913288.03
#Sta/Elev= 30
  4624.4 1886.22  4803.5 1878.38  4832.5 1875.81  4879.7 1874.35  4914.2 1876.28
  4966.9 1871.22  4993.6 1871.13  4994.1 1870.63  5000.1 1871.13  5385.9 1875.41
  5391.8 1876.97  5407.2 1875.74  5413.1 1877.53  5428.5 1876.23  5434.4 1878.22
  5443.9 1877.25  5449.8 1880.13  5465.2 1878.18  5471.1 1881.02  5480.6 1879.90
  5486.5 1883.09  5501.9 1881.55  5507.7 1883.67  5523.2 1882.18  5529.0 1884.34
  5559.8 1884.07  5565.7 1885.28  5581.1 1884.75  5602.4 1886.54  5762.8 1891.27
#Mann=3,-1,0
  4624.4    0.05       0  4993.6    0.03       0  5000.1    0.05       0
Bank Sta=4993.6,5000.1
Exp/Cntr=0.3,0.1

Type RM Length L Ch R = 1,13942,291,291,291
BEGIN DESCRIPTION:
Mapping XS 3a1777e1
END DESCRIPTION:
XS GIS Cut Line= 4
      1669624.88      6912352.92      1669762.89      6912483.12
      1669755.07      6913097.70      1669893.08      6913292.99
#Sta/Elev= 30
  4611.4 1888.10  4678.9 1884.54  4699.9 1882.71  4728.3 1881.33  4806.1 1878.66
  4866.0 1875.90  4886.0 1874.18  4916.0 1873.21  4926.0 1872.36  4936.0 1870.98
  4946.0 1870.46  4976.0 1869.87  5006.0 1869.89  5024.6 1870.32  5052.8 1869.62
  5053.3 1869.12  5058.8 1869.12  5059.3 1869.62  5096.0 1870.78  5156.0 1871.40
  5306.1 1871.30  5406.1 1871.95  5473.8 1873.99  5479.9 1873.70  5524.2 1874.02
  5566.1 1875.36  5595.6 1875.42  5601.8 1875.96  5652.2 1876.83  5654.9 1877.14
#Mann=3,-1,0
  4611.4    0.05       0  5052.8    0.05       0  5059.3    0.05       0
Bank Sta=5052.8,5059.3
Exp/Cntr=0.3,0.1

Type RM Length L Ch R = 1,13651,449,449,449
BEGIN DESCRIPTION:
Deadman 34 27.0
END DESCRIPTION:
XS GIS Cut Line= 3
      1669455.00      6912488.01      1669555.00      6912888.00
      1669966.01      6913548.22
#Sta/Elev= 30
  4588.3 1886.37  4619.2 1883.83  4670.7 1881.24  4742.9 1876.30  4804.7 1873.13
  4853.7 1869.39  4918.1 1868.29  4936.2 1866.40  4956.1 1865.20  4956.6 1864.70
  4962.1 1864.70  4962.6 1865.20  4977.4 1865.66  4990.3 1866.74  5008.3 1867.12
  5050.8 1869.83  5081.5 1870.45  5160.5 1870.26  5254.9 1870.88  5276.2 1871.86
  5306.9 1871.39  5328.1 1871.84  5334.0 1872.51  5349.4 1872.39  5377.5 1874.08
  5495.3 1875.65  5705.8 1880.19  5742.4 1881.95  5763.6 1882.38  5778.3 1883.45
#Mann=3,-1,0
  4588.3    0.05       0  4956.1    0.03       0  4962.6    0.05       0
Bank Sta=4956.1,4962.6
Exp/Cntr=0.3,0.1

Type RM Length L Ch R = 1,13202,465,465,465
BEGIN DESCRIPTION:
Deadman 34 26.0
END DESCRIPTION:
XS GIS Cut Line= 3
      1668905.01      6912738.02      1669205.00      6913138.00
      1670004.97      6913937.97
#Sta/Elev= 30
  4500.1 1882.17  4507.4 1881.33  4542.8 1879.16  4557.4 1877.58  4592.8 1876.20
  4607.4 1874.55  4657.4 1872.55  4700.1 1871.62  4707.4 1870.91  4842.8 1868.89
  4900.1 1867.08  4928.2 1866.79  4936.5 1866.38  4950.1 1863.85  4960.3 1862.90
  4960.8 1862.40  4966.5 1862.40  4967.0 1862.90  4997.0 1864.84  5056.6 1865.70
  5099.1 1867.53  5339.5 1869.64  5466.8 1873.05  5565.8 1874.72  5721.3 1879.22
  5763.8 1879.95  5792.0 1881.73  5876.9 1884.79  5919.3 1887.01  6131.4 1894.04
#Mann=3,-1,0
  4500.1    0.05       0  4960.3    0.03       0  4967.0    0.05       0
Bank Sta=4960.3,4967
Exp/Cntr=0.3,0.1

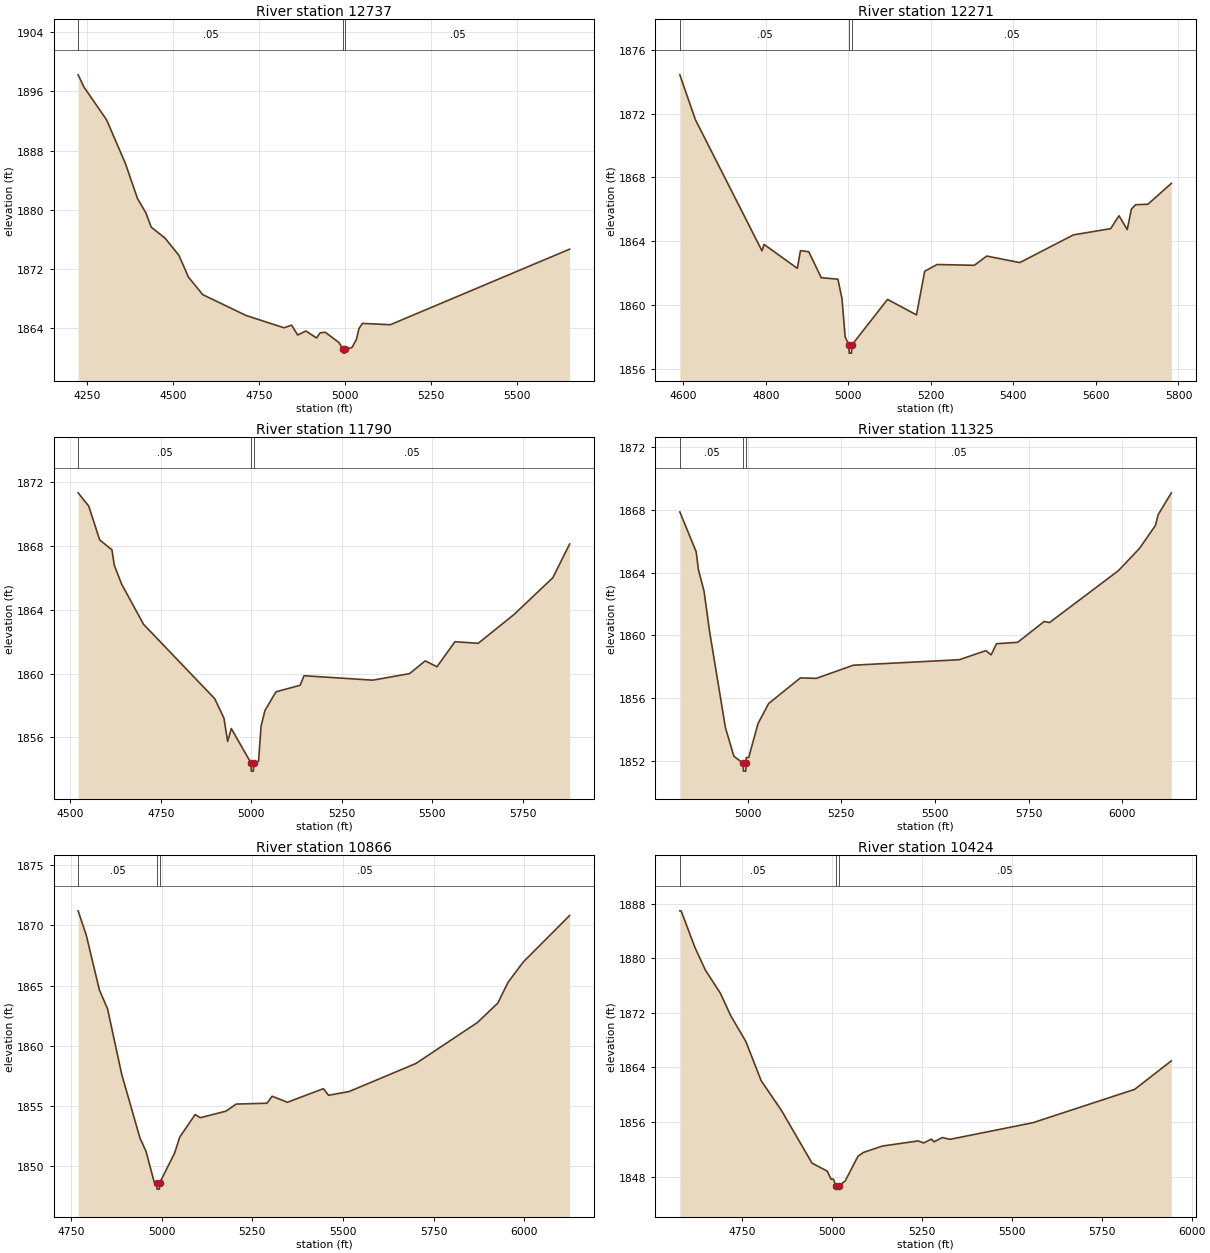
Type RM Length L Ch R = 1,12737,466,466,466
BEGIN DESCRIPTION:
Deadman 34 25.0
END DESCRIPTION:
XS GIS Cut Line= 3
      1668654.99      6912637.97      1668855.00      6913388.00
      1668960.81      6914032.63
#Sta/Elev= 30
  4223.5 1898.24  4241.0 1896.55  4306.3 1892.16  4361.3 1886.23  4396.2 1881.52
  4420.2 1879.62  4436.3 1877.65  4476.4 1876.17  4516.6 1873.85  4544.4 1870.90
  4585.8 1868.54  4711.9 1865.72  4821.9 1864.06  4844.5 1864.41  4862.0 1863.08
  4885.9 1863.62  4916.9 1862.68  4927.3 1863.37  4942.2 1863.45  4982.3 1862.06
  4993.8 1861.13  4994.3 1860.63  5000.0 1860.63  5000.5 1861.13  5020.0 1861.39
  5032.9 1862.48  5040.3 1863.94  5050.4 1864.65  5131.5 1864.47  5653.0 1874.68
#Mann=3,-1,0
  4223.5    0.05       0  4993.8    0.03       0  5000.5    0.05       0
Bank Sta=4993.8,5000.5
Exp/Cntr=0.3,0.1

Type RM Length L Ch R = 1,12271,481,481,481
BEGIN DESCRIPTION:
Deadman 34 24.0
END DESCRIPTION:
XS GIS Cut Line= 3
      1668355.00      6912937.99      1668405.00      6913338.00
      1668447.69      6914124.72
#Sta/Elev= 30
  4591.7 1874.43  4629.5 1871.61  4790.7 1863.39  4795.8 1863.79  4876.4 1862.29
  4884.0 1863.40  4904.1 1863.33  4934.4 1861.70  4974.7 1861.61  4984.7 1860.37
  4992.3 1857.98  5001.4 1857.47  5001.9 1856.97  5007.7 1856.97  5008.2 1857.47
  5095.0 1860.34  5165.1 1859.37  5185.1 1862.11  5215.1 1862.53  5305.3 1862.48
  5335.3 1863.06  5415.4 1862.65  5545.6 1864.39  5635.7 1864.78  5655.8 1865.59
  5675.8 1864.72  5685.8 1866.00  5695.9 1866.28  5725.9 1866.31  5782.7 1867.62
#Mann=3,-1,0
  4591.7    0.05       0  5001.4    0.03       0  5008.2    0.05       0
Bank Sta=5001.4,5008.2
Exp/Cntr=0.3,0.1

Type RM Length L Ch R = 1,11790,465,465,465
BEGIN DESCRIPTION:
Deadman 34 23.0
END DESCRIPTION:
XS GIS Cut Line= 4
      1668022.89      6912958.96      1667955.00      6913438.00
      1668150.49      6913917.33      1668375.20      6914193.98
#Sta/Elev= 30
  4521.3 1871.33  4550.6 1870.50  4580.9 1868.38  4614.7 1867.76  4621.3 1866.79
  4641.5 1865.61  4702.1 1863.09  4898.7 1858.43  4924.3 1857.20  4934.4 1855.75
  4944.5 1856.56  4999.2 1854.39  4999.7 1853.89  5005.5 1853.89  5006.0 1854.39
  5019.8 1854.51  5026.7 1856.70  5037.5 1857.69  5067.9 1858.86  5134.7 1859.27
  5145.4 1859.87  5335.3 1859.59  5436.9 1860.00  5480.3 1860.80  5512.7 1860.43
  5562.3 1862.00  5626.7 1861.90  5725.8 1863.71  5832.8 1866.01  5879.2 1868.12
#Mann=3,-1,0
  4521.3    0.05       0  4999.2    0.03       0  5006.0    0.05       0
Bank Sta=4999.2,5006
Exp/Cntr=0.3,0.1

Type RM Length L Ch R = 1,11325,459,459,459
BEGIN DESCRIPTION:
Deadman 34 22.0
END DESCRIPTION:
XS GIS Cut Line= 3
      1667405.00      6913338.00      1667555.00      6913438.00
      1668354.97      6914237.97
#Sta/Elev= 30
  4819.1 1867.87  4862.7 1865.33  4868.7 1864.19  4883.7 1862.81  4898.7 1860.21
  4940.8 1854.10  4963.3 1852.28  4988.2 1851.83  4988.7 1851.33  4995.0 1851.33
  4995.5 1851.83  4996.4 1852.20  5002.9 1852.20  5027.7 1854.36  5055.9 1855.64
  5140.8 1857.28  5183.2 1857.25  5282.2 1858.09  5565.1 1858.44  5635.8 1859.02
  5649.9 1858.75  5664.1 1859.46  5720.6 1859.55  5791.3 1860.88  5805.5 1860.81
  5989.3 1864.12  6045.9 1865.55  6088.3 1867.01  6095.4 1867.69  6130.7 1869.09
#Mann=3,-1,0
  4819.1    0.05       0  4988.2    0.05       0  4995.5    0.05       0
Bank Sta=4988.2,4995.5
Exp/Cntr=0.3,0.1

Type RM Length L Ch R = 1,10866,442,442,442
BEGIN DESCRIPTION:
Deadman 34 21.0
END DESCRIPTION:
XS GIS Cut Line= 3
      1667104.97      6913687.99      1667305.00      6913788.00
      1668104.99      6914587.99
#Sta/Elev= 30
  4769.8 1871.21  4792.2 1869.20  4828.5 1864.64  4850.9 1863.08  4890.0 1857.64
  4940.3 1852.35  4957.1 1851.24  4979.5 1848.70  4986.9 1848.61  4987.4 1848.11
  4993.8 1848.11  4994.3 1848.61  5035.9 1851.11  5050.0 1852.43  5092.4 1854.30
  5106.6 1854.04  5177.3 1854.58  5205.6 1855.17  5290.4 1855.24  5304.6 1855.82
  5347.0 1855.32  5446.0 1856.45  5460.1 1855.90  5516.7 1856.21  5700.5 1858.53
  5870.2 1861.93  5926.8 1863.55  5955.1 1865.28  5997.5 1866.98  6124.8 1870.82
#Mann=3,-1,0
  4769.8    0.05       0  4986.9    0.03       0  4994.3    0.05       0
Bank Sta=4986.9,4994.3
Exp/Cntr=0.3,0.1

Type RM Length L Ch R = 1,10424,438,438,438
BEGIN DESCRIPTION:
Deadman 34 20.0
END DESCRIPTION:
XS GIS Cut Line= 3
      1666754.97      6913837.97      1667055.00      6914138.00
      1667854.99      6914638.00
#Sta/Elev= 30
  4575.8 1886.95  4579.4 1886.95  4618.3 1881.52  4646.6 1878.29  4689.0 1874.83
  4717.3 1871.59  4759.7 1867.77  4802.1 1862.05  4858.7 1857.68  4943.5 1849.97
  4986.0 1848.79  4996.6 1847.61  5003.1 1847.61  5010.0 1846.65  5010.5 1846.15
  5016.9 1846.15  5017.4 1846.65  5035.5 1847.31  5071.5 1850.97  5086.8 1851.53
  5138.7 1852.46  5238.9 1853.22  5254.2 1852.92  5275.5 1853.48  5283.1 1853.09
  5306.1 1853.71  5327.4 1853.45  5558.5 1855.89  5841.5 1860.78  5943.5 1864.96
#Mann=3,-1,0
  4575.8    0.05       0  5010.0    0.03       0  5017.4    0.05       0
Bank Sta=5010,5017.4
Exp/Cntr=0.3,0.1

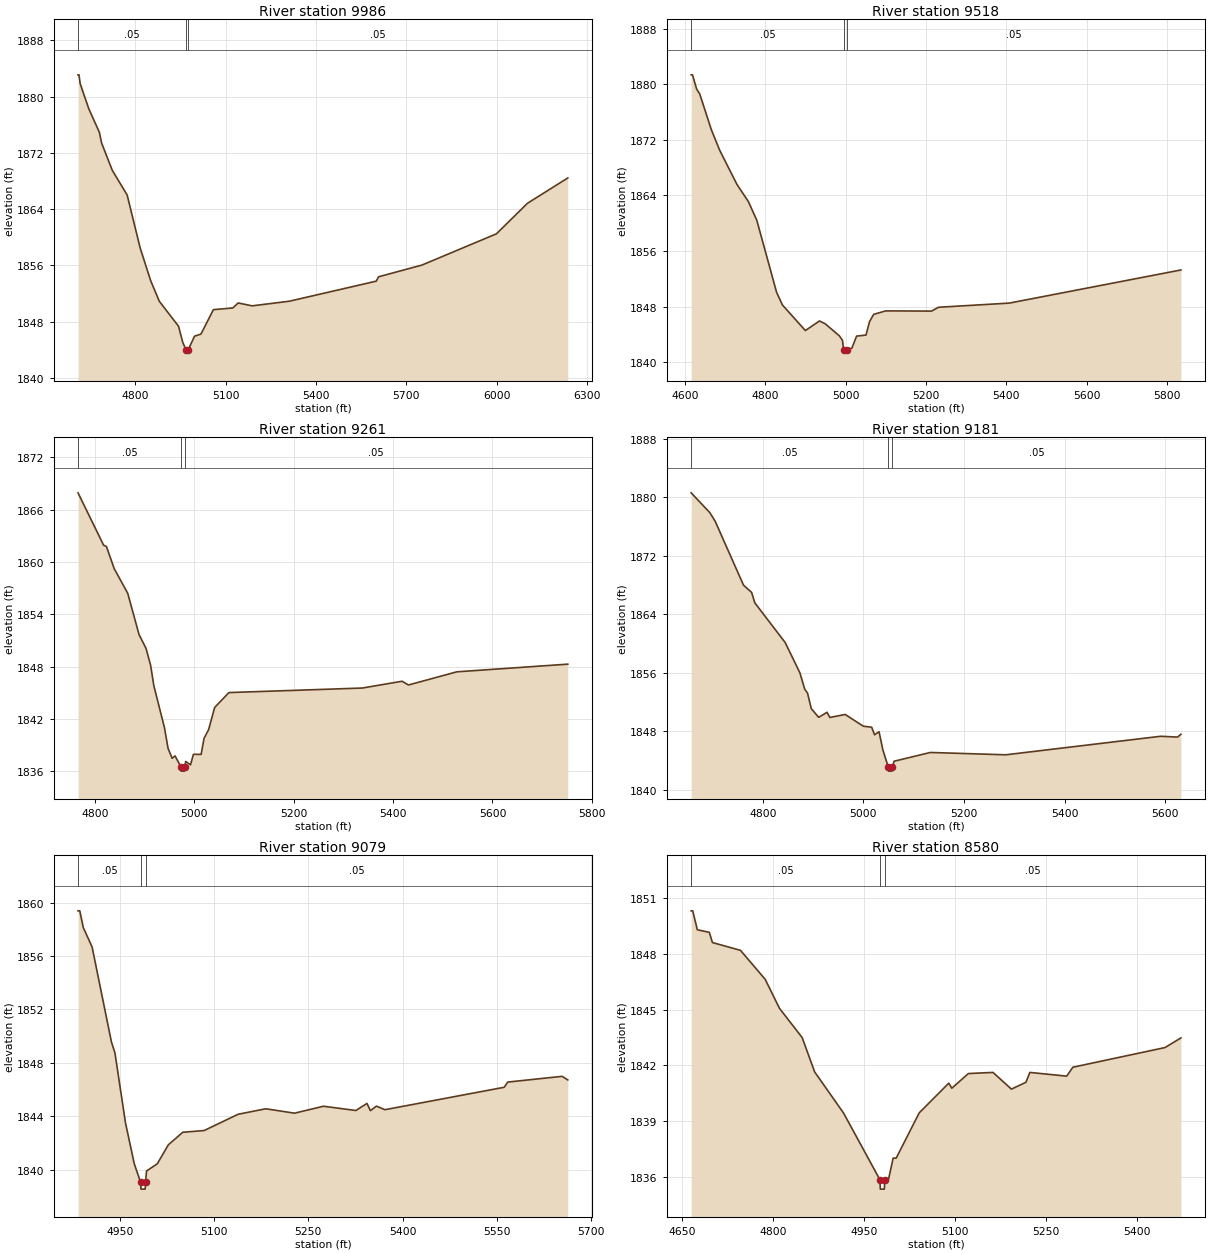
Type RM Length L Ch R = 1,9986,468,468,468
BEGIN DESCRIPTION:
Deadman 34 19.0
END DESCRIPTION:
XS GIS Cut Line= 3
      1666505.01      6914138.01      1666755.00      6914438.00
      1667954.97      6914737.99
#Sta/Elev= 30
  4609.4 1883.10  4612.6 1883.10  4616.5 1881.85  4645.2 1878.27  4680.3 1874.94
  4687.5 1873.43  4723.3 1869.52  4772.7 1866.01  4815.7 1858.51  4850.8 1853.84
  4879.5 1850.91  4943.3 1847.37  4957.6 1845.04  4968.1 1844.04  4968.6 1843.54
  4975.2 1843.54  4975.7 1844.04  4996.6 1845.95  5017.9 1846.25  5059.2 1849.72
  5123.6 1849.96  5141.6 1850.67  5188.0 1850.26  5311.7 1850.92  5600.3 1853.77
  5608.1 1854.39  5752.4 1856.06  5999.7 1860.50  6102.8 1864.84  6236.8 1868.44
#Mann=3,-1,0
  4609.4    0.05       0  4968.1    0.03       0  4975.7    0.05       0
Bank Sta=4968.1,4975.7
Exp/Cntr=0.3,0.1

Type RM Length L Ch R = 1,9518,257,257,257
BEGIN DESCRIPTION:
Deadman 34 18.0
END DESCRIPTION:
XS GIS Cut Line= 3
      1666205.00      6914487.99      1666455.00      6914788.00
      1667227.88      6915088.06
#Sta/Elev= 30
  4615.0 1881.37  4618.3 1881.37  4628.7 1879.32  4636.5 1878.60  4665.1 1873.50
  4686.0 1870.52  4728.9 1865.61  4757.5 1863.13  4778.4 1860.45  4827.8 1850.06
  4842.2 1848.25  4899.4 1844.56  4934.6 1845.94  4948.9 1845.53  4984.0 1843.80
  4991.9 1843.14  4994.6 1841.81  4995.1 1841.31  5001.7 1841.31  5002.2 1841.81
  5015.1 1842.02  5027.0 1843.76  5050.4 1843.91  5059.2 1845.85  5069.6 1846.89
  5099.5 1847.39  5213.7 1847.36  5230.8 1847.91  5407.0 1848.51  5834.6 1853.28
#Mann=3,-1,0
  4615.0    0.05       0  4994.6    0.03       0  5002.2    0.05       0
Bank Sta=4994.6,5002.2
Exp/Cntr=0.3,0.1

Type RM Length L Ch R = 1,9261,80,80,80
BEGIN DESCRIPTION:
Mapping XS d87f0fb5
END DESCRIPTION:
XS GIS Cut Line= 4
      1666059.74      6914824.25      1666320.18      6914980.51
      1666692.57      6915186.24      1666916.86      6915310.15
#Sta/Elev= 30
  4766.2 1867.93  4817.6 1861.93  4823.4 1861.77  4839.0 1859.23  4866.2 1856.41
  4888.9 1851.68  4903.1 1850.08  4912.3 1848.14  4918.7 1845.82  4940.1 1840.99
  4947.3 1838.63  4955.6 1837.48  4961.4 1837.76  4973.1 1836.51  4973.6 1836.01
  4980.3 1836.01  4980.8 1836.51  4982.8 1837.12  4992.5 1836.73  4998.4 1837.94
  5013.9 1837.93  5019.7 1839.77  5028.9 1840.76  5041.1 1843.31  5069.8 1845.02
  5338.2 1845.54  5418.2 1846.32  5431.0 1845.89  5528.4 1847.40  5751.6 1848.28
#Mann=3,-1,0
  4766.2    0.05       0  4973.1    0.05       0  4980.8    0.05       0
Bank Sta=4973.1,4980.8
Exp/Cntr=0.3,0.1

Type RM Length L Ch R = 1,9181,102,102,102
BEGIN DESCRIPTION:
Mapping XS 6c6075bb
END DESCRIPTION:
XS GIS Cut Line= 3
      1665922.31      6914858.49      1666486.52      6915147.10
      1666791.29      6915298.40
#Sta/Elev= 30
  4657.5 1880.58  4694.6 1877.88  4705.4 1876.68  4761.6 1867.97  4777.8 1866.97
  4784.1 1865.55  4844.5 1860.13  4873.9 1855.97  4883.3 1853.76  4888.9 1853.23
  4896.4 1851.10  4911.1 1849.91  4927.7 1850.60  4933.3 1849.89  4963.8 1850.30
  4999.9 1848.70  5016.5 1848.56  5022.2 1847.53  5031.2 1847.94  5038.7 1845.48
  5049.8 1843.06  5050.3 1842.56  5057.0 1842.56  5057.5 1843.06  5061.0 1843.91
  5133.2 1845.11  5283.1 1844.79  5591.0 1847.32  5624.7 1847.21  5631.5 1847.60
#Mann=3,-1,0
  4657.5    0.05       0  5049.8    0.03       0  5057.5    0.05       0
Bank Sta=5049.8,5057.5
Exp/Cntr=0.3,0.1

Type RM Length L Ch R = 1,9079,499,499,499
BEGIN DESCRIPTION:
Deadman 34 17.0
END DESCRIPTION:
XS GIS Cut Line= 3
      1666055.01      6915038.00      1666155.00      6915088.00
      1666761.83      6915365.10
#Sta/Elev= 30
  4883.8 1859.38  4886.6 1859.38  4892.2 1858.12  4906.2 1856.67  4936.9 1849.56
  4942.5 1848.74  4959.3 1843.49  4973.2 1840.44  4983.4 1839.03  4983.9 1838.53
  4990.6 1838.53  4991.1 1839.03  4992.8 1839.89  5009.9 1840.43  5027.4 1841.85
  5050.4 1842.79  5084.4 1842.92  5138.5 1844.14  5182.5 1844.55  5228.1 1844.22
  5274.2 1844.74  5325.7 1844.42  5343.3 1844.95  5348.8 1844.41  5358.4 1844.75
  5371.8 1844.48  5561.5 1846.16  5567.2 1846.55  5653.7 1846.98  5662.7 1846.71
#Mann=3,-1,0
  4883.8    0.05       0  4983.4    0.03       0  4991.1    0.05       0
Bank Sta=4983.4,4991.1
Exp/Cntr=0.3,0.1

Type RM Length L Ch R = 1,8580,466,466,466
BEGIN DESCRIPTION:
Deadman 34 16.0
END DESCRIPTION:
XS GIS Cut Line= 3
      1665824.95      6915526.70      1666155.00      6915588.00
      1666620.92      6915511.23
#Sta/Elev= 30
  4664.4 1850.32  4667.0 1850.32  4674.6 1849.30  4694.4 1849.16  4699.5 1848.61
  4745.8 1848.19  4786.5 1846.63  4810.2 1845.06  4847.5 1843.49  4868.1 1841.64
  4915.8 1839.42  4975.9 1835.82  4976.4 1835.32  4983.1 1835.32  4983.6 1835.82
  4989.9 1835.84  4997.6 1836.99  5002.6 1836.99  5040.6 1839.43  5089.3 1841.03
  5094.4 1840.76  5121.7 1841.55  5162.3 1841.61  5192.7 1840.71  5216.7 1841.08
  5223.1 1841.61  5283.9 1841.41  5294.0 1841.89  5446.0 1842.95  5472.3 1843.47
#Mann=3,-1,0
  4664.4    0.05       0  4975.9    0.03       0  4983.6    0.05       0
Bank Sta=4975.9,4983.6
Exp/Cntr=0.3,0.1