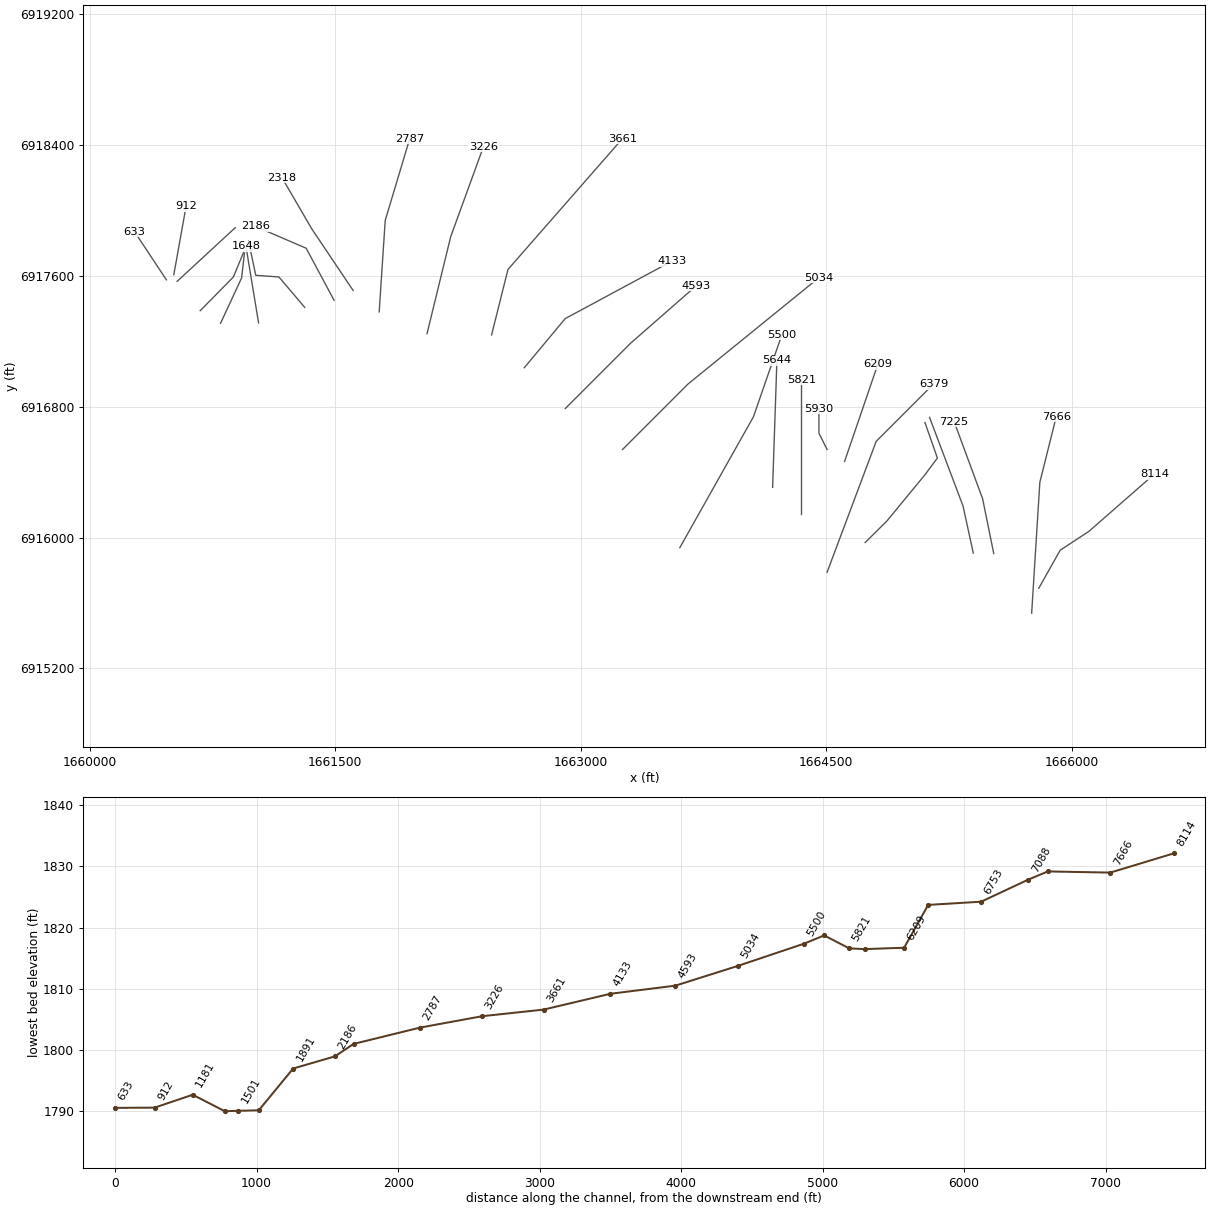
HEC-RAS study Deadman 34.prj: Deadman 34 Base Level Engineering

--- Deadman 34.g01 (geometry) --- (continued)

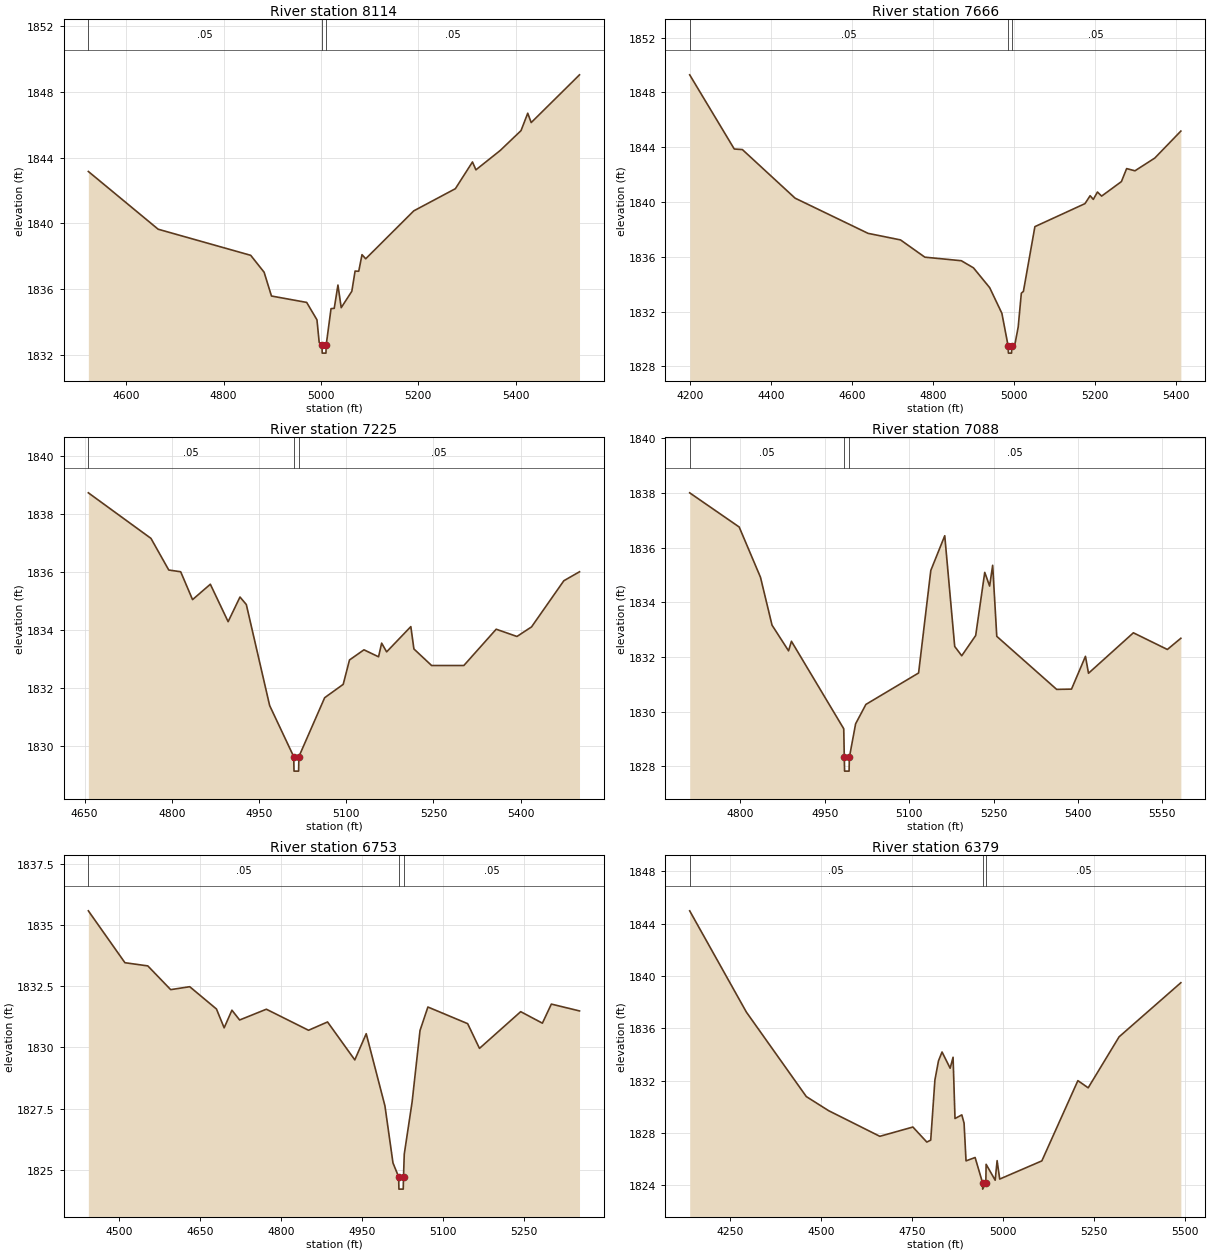
Type RM Length L Ch R = 1,8114,448,448,448
BEGIN DESCRIPTION:
Deadman 34 15.0
END DESCRIPTION:
XS GIS Cut Line= 4
      1665798.43      6915690.21      1665929.14      6915922.53
      1666105.00      6916038.00      1666505.04      6916388.03
#Sta/Elev= 30
  4522.4 1843.16  4665.8 1839.64  4855.8 1838.05  4883.3 1837.02  4898.4 1835.57
  4970.7 1835.18  4991.8 1834.12  4996.4 1832.74  5002.1 1832.59  5002.6 1832.09
  5010.3 1832.09  5010.8 1832.59  5020.7 1834.80  5027.3 1834.82  5034.9 1836.24
  5041.6 1834.86  5063.4 1835.86  5070.1 1837.09  5077.6 1837.08  5084.3 1838.09
  5091.9 1837.84  5190.6 1840.76  5276.0 1842.11  5311.1 1843.74  5318.2 1843.26
  5368.1 1844.44  5410.8 1845.65  5424.6 1846.71  5431.7 1846.14  5530.9 1849.05
#Mann=3,-1,0
  4522.4    0.05       0  5002.1    0.03       0  5010.8    0.05       0
Bank Sta=5002.1,5010.8
Exp/Cntr=0.3,0.1

Type RM Length L Ch R = 1,7666,441,441,441
BEGIN DESCRIPTION:
Deadman 34 14.0
END DESCRIPTION:
XS GIS Cut Line= 3
      1665755.00      6915538.04      1665805.00      6916338.00
      1665904.99      6916737.97
#Sta/Elev= 30
  4198.2 1849.29  4308.4 1843.87  4328.4 1843.83  4458.7 1840.28  4639.0 1837.71
  4719.2 1837.23  4779.3 1835.97  4869.5 1835.71  4899.5 1835.19  4939.6 1833.74
  4969.7 1831.87  4985.3 1829.46  4985.8 1828.96  4993.6 1828.96  4994.1 1829.46
  5002.3 1829.67  5010.0 1830.86  5017.8 1833.34  5022.9 1833.47  5051.3 1838.20
  5175.0 1839.88  5187.8 1840.46  5195.6 1840.19  5205.9 1840.73  5216.2 1840.43
  5265.1 1841.49  5278.0 1842.44  5298.6 1842.28  5347.6 1843.21  5412.0 1845.18
#Mann=3,-1,0
  4198.2    0.05       0  4985.3    0.03       0  4994.1    0.05       0
Bank Sta=4985.3,4994.1
Exp/Cntr=0.3,0.1

Type RM Length L Ch R = 1,7225,137,137,137
BEGIN DESCRIPTION:
Deadman 34 13.0
END DESCRIPTION:
XS GIS Cut Line= 4
      1665523.29      6915902.43      1665455.00      6916238.00
      1665320.18      6916602.91      1665280.93      6916709.12
#Sta/Elev= 30
  4656.5 1838.74  4764.2 1837.17  4794.8 1836.08  4815.3 1836.02  4835.7 1835.06
  4866.3 1835.59  4896.9 1834.30  4917.3 1835.15  4928.2 1834.89  4968.3 1831.41
  5009.7 1829.65  5010.2 1829.15  5018.1 1829.15  5018.6 1829.65  5062.9 1831.68
  5094.8 1832.14  5105.6 1832.98  5130.5 1833.33  5155.6 1833.09  5160.9 1833.56
  5169.5 1833.26  5211.1 1834.13  5216.4 1833.36  5246.8 1832.79  5302.3 1832.79
  5357.9 1834.04  5393.6 1833.79  5418.7 1834.12  5474.2 1835.71  5501.2 1836.02
#Mann=3,-1,0
  4656.5    0.05       0  5009.7    0.03       0  5018.6    0.05       0
Bank Sta=5009.7,5018.6
Exp/Cntr=0.3,0.1

Type RM Length L Ch R = 1,7088,335,335,335
BEGIN DESCRIPTION:
Mapping XS 0ca307e7
END DESCRIPTION:
XS GIS Cut Line= 4
      1665398.30      6915904.99      1665335.39      6916193.37
      1665208.20      6916529.99      1665131.04      6916734.19
#Sta/Elev= 30
  4709.8 1838.01  4797.8 1836.76  4835.7 1834.92  4856.2 1833.17  4885.6 1832.23
  4890.7 1832.58  4983.7 1829.38  4984.7 1828.33  4985.2 1827.83  4993.2 1827.83
  4993.7 1828.33  5004.8 1829.56  5023.1 1830.27  5116.8 1831.42  5138.5 1835.17
  5163.3 1836.44  5181.0 1832.39  5193.5 1832.05  5218.3 1832.79  5234.4 1835.10
  5243.1 1834.60  5248.5 1835.36  5255.8 1832.76  5362.3 1830.82  5388.7 1830.83
  5413.5 1832.03  5418.9 1831.41  5498.7 1832.89  5559.1 1832.28  5583.1 1832.69
#Mann=3,-1,0
  4709.8    0.05       0  4984.7    0.03       0  4993.7    0.05       0
Bank Sta=4984.7,4993.7
Exp/Cntr=0.3,0.1

Type RM Length L Ch R = 1,6753,374,374,374
BEGIN DESCRIPTION:
Deadman 34 12.0
END DESCRIPTION:
XS GIS Cut Line= 5
      1664737.58      6915969.54      1664869.66      6916100.30
      1665101.85      6916382.26      1665179.00      6916485.86
      1665102.97      6916702.94
#Sta/Elev= 30
  4443.5 1835.58  4511.3 1833.46  4553.7 1833.33  4596.1 1832.36  4631.4 1832.48
  4680.9 1831.57  4695.2 1830.80  4709.6 1831.52  4723.9 1831.12  4773.4 1831.56
  4851.6 1830.70  4886.8 1831.04  4937.3 1829.49  4958.5 1830.56  4993.2 1827.61
  5008.1 1825.28  5018.6 1824.71  5019.1 1824.21  5027.1 1824.21  5027.6 1824.71
  5029.0 1825.64  5043.6 1827.78  5058.2 1830.69  5072.8 1831.65  5146.5 1830.97
  5168.4 1829.96  5244.8 1831.46  5285.0 1830.99  5301.6 1831.77  5353.8 1831.49
#Mann=3,-1,0
  4443.5    0.05       0  5018.6    0.03       0  5027.6    0.05       0
Bank Sta=5018.6,5027.6
Exp/Cntr=0.3,0.1

Type RM Length L Ch R = 1,6379,170,170,170
BEGIN DESCRIPTION:
Deadman 34 11.0
END DESCRIPTION:
XS GIS Cut Line= 3
      1664505.00      6915787.99      1664805.00      6916588.00
      1665155.01      6916938.01
#Sta/Elev= 30
  4139.1 1844.98  4294.9 1837.23  4459.5 1830.77  4520.9 1829.69  4661.5 1827.73
  4752.3 1828.44  4790.6 1827.29  4801.3 1827.44  4812.8 1832.04  4822.6 1833.50
  4832.4 1834.18  4854.7 1832.94  4862.7 1833.78  4868.0 1829.09  4886.7 1829.37
  4892.9 1828.74  4898.3 1825.85  4923.2 1826.11  4943.6 1824.19  4944.1 1823.69
  4952.7 1824.19  4953.5 1825.59  4978.4 1824.37  4983.7 1825.87  4990.8 1824.46
  5106.6 1825.85  5205.6 1831.99  5233.9 1831.44  5318.8 1835.34  5488.5 1839.48
#Mann=3,-1,0
  4139.1    0.05       0  4943.6    0.03       0  4952.7    0.05       0
Bank Sta=4943.6,4952.7
Exp/Cntr=0.3,0.1

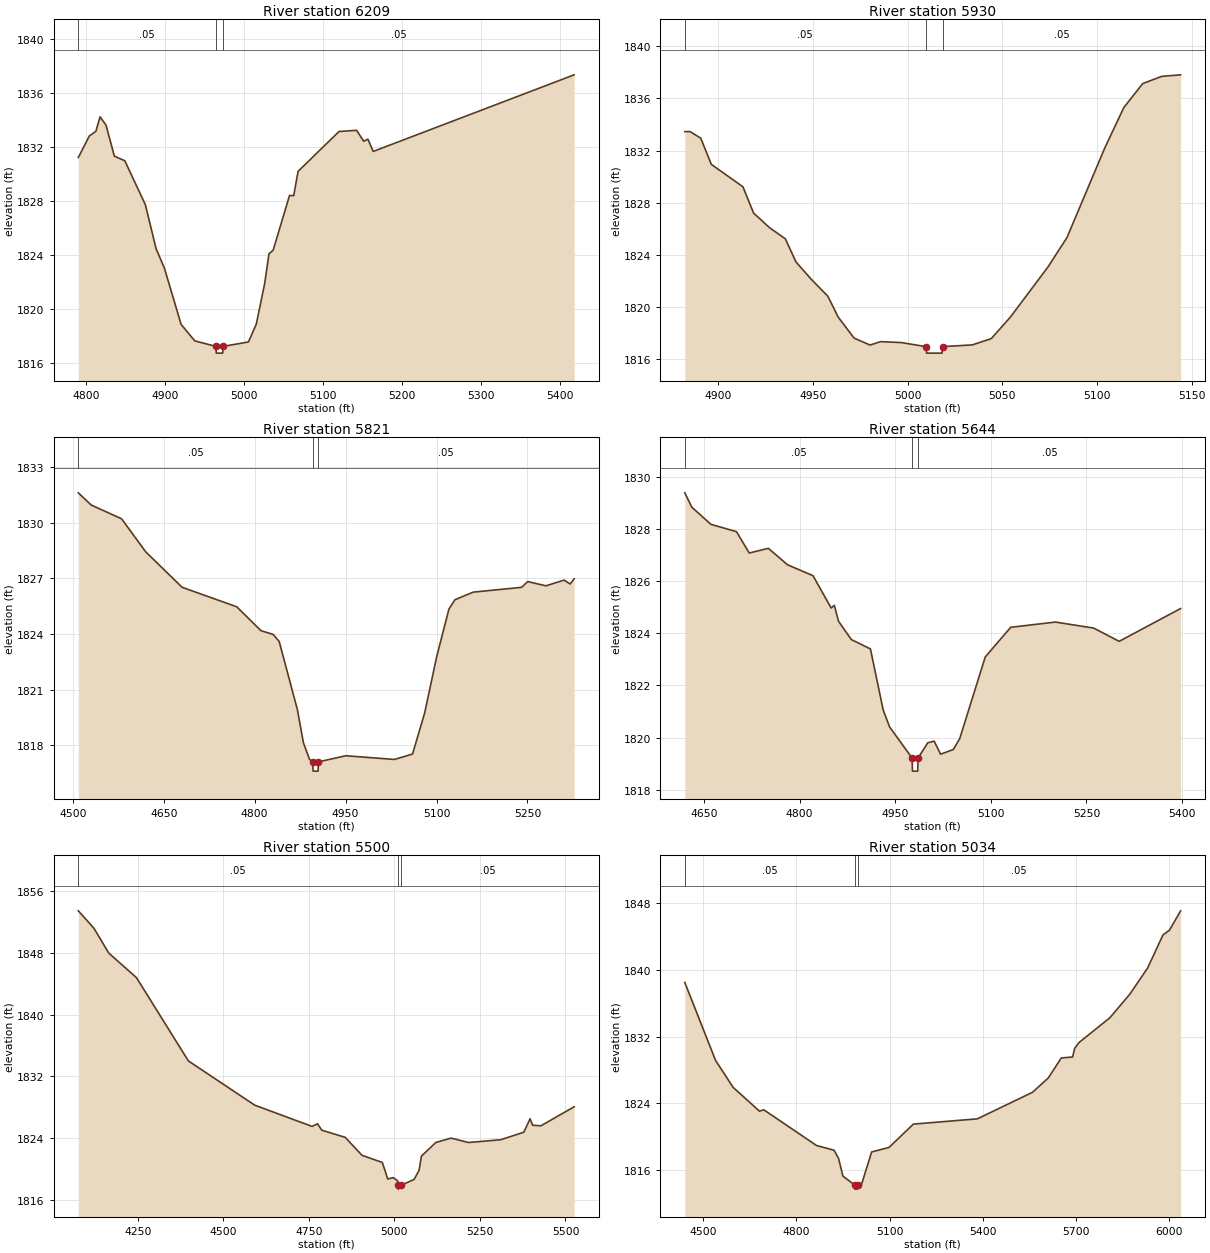
Type RM Length L Ch R = 1,6209,279,279,279
BEGIN DESCRIPTION:
Mapping XS c889b7f4
END DESCRIPTION:
XS GIS Cut Line= 2
      1664611.84      6916464.89      1664814.96      6917058.61
#Sta/Elev= 30
  4790.0 1831.23  4803.9 1832.83  4812.2 1833.17  4817.5 1834.25  4825.0 1833.64
  4835.6 1831.33  4848.8 1830.99  4874.8 1827.73  4888.4 1824.46  4899.0 1823.00
  4920.1 1818.83  4937.4 1817.61  4964.1 1817.20  4964.6 1816.70  4972.7 1816.70
  4973.2 1817.20  5005.3 1817.53  5015.2 1818.85  5025.8 1821.86  5031.3 1824.08
  5036.6 1824.35  5057.3 1828.41  5062.6 1828.40  5068.1 1830.20  5119.9 1833.16
  5142.1 1833.25  5151.2 1832.44  5156.5 1832.59  5163.2 1831.68  5417.5 1837.37
#Mann=3,-1,0
  4790.0    0.05       0  4964.1    0.03       0  4973.2    0.05       0
Bank Sta=4964.1,4973.2
Exp/Cntr=0.3,0.1

Type RM Length L Ch R = 1,5930,109,109,109
BEGIN DESCRIPTION:
Deadman 34 10.0
END DESCRIPTION:
XS GIS Cut Line= 3
      1664505.00      6916538.01      1664455.00      6916638.00
      1664455.00      6916788.01
#Sta/Elev= 30
  4882.4 1833.46  4885.2 1833.46  4890.8 1832.96  4896.4 1830.95  4913.1 1829.23
  4918.7 1827.22  4927.1 1826.10  4935.5 1825.24  4941.1 1823.47  4949.5 1822.09
  4957.9 1820.85  4963.4 1819.24  4971.8 1817.63  4980.2 1817.10  4985.8 1817.36
  4996.7 1817.29  5009.6 1816.98  5010.1 1816.48  5018.2 1816.48  5018.7 1816.98
  5034.2 1817.11  5044.2 1817.59  5054.2 1819.22  5074.2 1823.09  5084.2 1825.34
  5104.2 1832.22  5114.2 1835.30  5124.2 1837.14  5134.2 1837.69  5144.2 1837.81
#Mann=3,-1,0
  4882.4    0.05       0  5009.6    0.05       0  5018.7    0.05       0
Bank Sta=5009.6,5018.7
Exp/Cntr=0.3,0.1

Type RM Length L Ch R = 1,5821,177,177,177
BEGIN DESCRIPTION:
Mapping XS 3f8bceae
END DESCRIPTION:
XS GIS Cut Line= 2
      1664346.92      6916146.66      1664346.92      6916964.56
#Sta/Elev= 30
  4509.1 1831.62  4530.4 1830.96  4580.4 1830.22  4620.4 1828.43  4680.4 1826.52
  4770.4 1825.47  4810.4 1824.18  4830.4 1823.98  4840.4 1823.60  4870.4 1819.93
  4880.4 1818.13  4890.4 1817.24  4895.8 1817.10  4896.3 1816.60  4904.6 1816.60
  4905.1 1817.10  4950.4 1817.43  5030.4 1817.23  5060.4 1817.52  5080.4 1819.74
  5100.4 1822.80  5120.4 1825.34  5130.4 1825.85  5160.4 1826.26  5240.4 1826.52
  5250.4 1826.83  5280.4 1826.60  5310.4 1826.91  5320.4 1826.70  5327.0 1826.98
#Mann=3,-1,0
  4509.1    0.05       0  4895.8    0.05       0  4905.1    0.05       0
Bank Sta=4895.8,4905.1
Exp/Cntr=0.3,0.1

Type RM Length L Ch R = 1,5644,144,144,144
BEGIN DESCRIPTION:
Mapping XS 039ff796
END DESCRIPTION:
XS GIS Cut Line= 2
      1664172.09      6916306.98      1664198.47      6917084.33
#Sta/Elev= 30
  4619.9 1829.39  4630.9 1828.84  4660.9 1828.18  4701.0 1827.90  4721.0 1827.08
  4751.0 1827.26  4781.0 1826.63  4821.0 1826.21  4849.5 1824.97  4854.5 1825.07
  4861.1 1824.46  4881.1 1823.76  4911.1 1823.40  4931.1 1821.06  4941.1 1820.41
  4976.5 1819.21  4977.0 1818.71  4985.3 1818.71  4985.8 1819.21  5001.1 1819.80
  5011.1 1819.86  5021.2 1819.36  5041.2 1819.54  5051.2 1819.96  5091.2 1823.09
  5131.2 1824.23  5201.3 1824.43  5261.3 1824.20  5301.3 1823.69  5397.7 1824.95
#Mann=3,-1,0
  4619.9    0.05       0  4976.5    0.03       0  4985.8    0.05       0
Bank Sta=4976.5,4985.8
Exp/Cntr=0.3,0.1

Type RM Length L Ch R = 1,5500,466,466,466
BEGIN DESCRIPTION:
Deadman 34 9.0
END DESCRIPTION:
XS GIS Cut Line= 3
      1663604.98      6915937.96      1664055.00      6916738.00
      1664228.89      6917239.69
#Sta/Elev= 30
  4076.5 1853.47  4122.1 1851.21  4165.5 1847.98  4246.4 1844.80  4398.1 1833.99
  4591.9 1828.25  4759.5 1825.49  4775.5 1825.83  4787.9 1825.00  4856.4 1824.07
  4905.5 1821.74  4964.8 1820.81  4980.7 1818.67  4997.1 1818.84  5010.0 1818.40
  5010.9 1817.85  5011.4 1817.35  5020.2 1817.85  5057.9 1818.62  5072.3 1819.80
  5079.1 1821.64  5121.4 1823.41  5165.7 1823.97  5216.7 1823.40  5310.8 1823.76
  5378.4 1824.74  5396.6 1826.48  5404.3 1825.64  5428.4 1825.57  5525.4 1828.04
#Mann=3,-1,0
  4076.5    0.05       0  5010.9    0.03       0  5020.2    0.05       0
Bank Sta=5010.9,5020.2
Exp/Cntr=0.3,0.1

Type RM Length L Ch R = 1,5034,441,441,441
BEGIN DESCRIPTION:
Deadman 34 8.0
END DESCRIPTION:
XS GIS Cut Line= 3
      1663255.02      6916538.02      1663655.00      6916938.00
      1664454.97      6917587.98
#Sta/Elev= 30
  4440.9 1838.47  4539.9 1829.15  4596.4 1825.92  4681.3 1823.07  4695.4 1823.23
  4865.1 1818.96  4921.7 1818.39  4935.9 1817.42  4950.0 1815.30  4987.7 1814.24
  4988.2 1813.74  4996.6 1813.74  4997.1 1814.24  5009.8 1814.29  5042.5 1818.19
  5098.5 1818.73  5176.8 1821.52  5382.9 1822.15  5560.6 1825.33  5611.4 1827.05
  5653.0 1829.43  5689.5 1829.55  5696.1 1830.58  5710.5 1831.29  5809.6 1834.25
  5873.6 1837.06  5931.0 1840.19  5980.6 1844.16  6001.4 1844.72  6037.3 1847.04
#Mann=3,-1,0
  4440.9    0.05       0  4987.7    0.03       0  4997.1    0.05       0
Bank Sta=4987.7,4997.1
Exp/Cntr=0.3,0.1

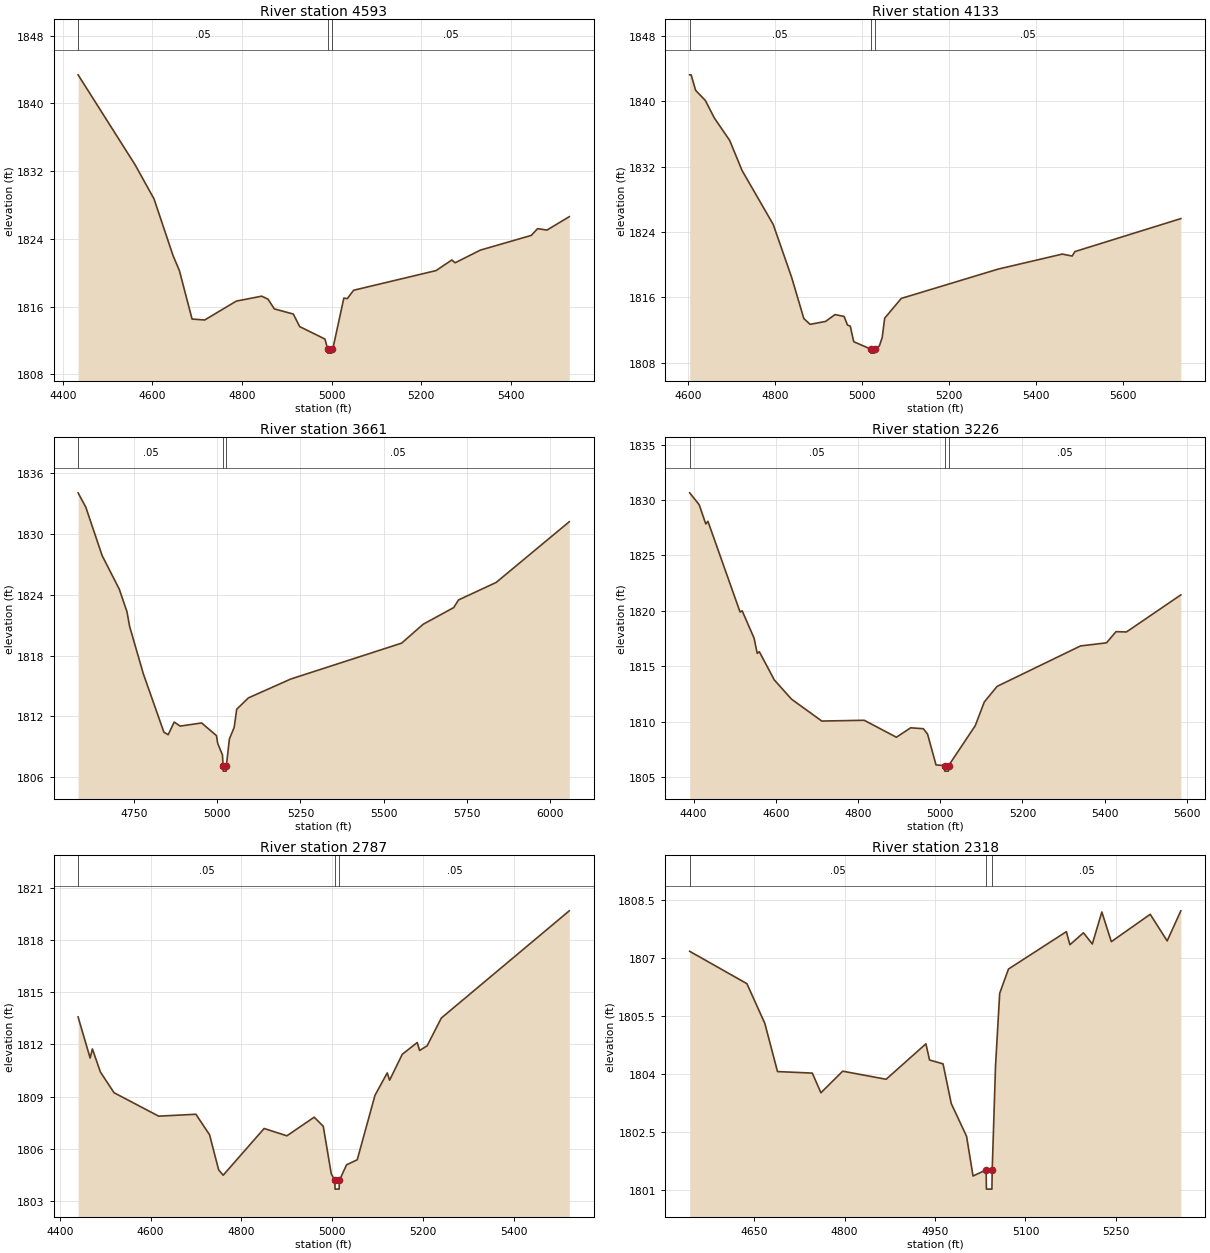
Type RM Length L Ch R = 1,4593,460,460,460
BEGIN DESCRIPTION:
Deadman 34 7.0
END DESCRIPTION:
XS GIS Cut Line= 3
      1662905.00      6916788.00      1663305.00      6917188.00
      1663705.01      6917538.01
#Sta/Elev= 30
  4433.9 1843.36  4561.2 1832.75  4603.6 1828.71  4646.0 1822.03  4660.2 1820.26
  4688.5 1814.54  4716.7 1814.43  4787.4 1816.66  4844.0 1817.24  4858.2 1816.89
  4872.3 1815.74  4914.7 1815.13  4928.9 1813.65  4985.4 1812.18  4991.2 1811.02
  4991.7 1810.52  5000.3 1810.52  5000.8 1811.02  5002.9 1811.02  5027.6 1817.02
  5035.2 1816.95  5049.4 1817.94  5233.5 1820.26  5268.7 1821.51  5276.2 1821.18
  5332.2 1822.67  5446.1 1824.41  5460.4 1825.21  5481.3 1825.04  5531.1 1826.62
#Mann=3,-1,0
  4433.9    0.05       0  4991.2    0.03       0  5000.8    0.05       0
Bank Sta=4991.2,5000.8
Exp/Cntr=0.3,0.1

Type RM Length L Ch R = 1,4133,472,472,472
BEGIN DESCRIPTION:
Deadman 34 6.0
END DESCRIPTION:
XS GIS Cut Line= 3
      1662654.98      6917037.97      1662905.00      6917338.00
      1663555.01      6917688.00
#Sta/Elev= 30
  4603.6 1843.22  4606.9 1843.22  4617.3 1841.32  4639.4 1840.10  4660.3 1837.94
  4695.4 1835.21  4724.0 1831.52  4795.6 1824.92  4837.9 1818.46  4865.9 1813.42
  4880.3 1812.71  4916.0 1813.07  4937.5 1813.90  4958.4 1813.68  4966.2 1812.63
  4972.7 1812.49  4980.5 1810.59  5019.4 1809.69  5019.9 1809.19  5028.5 1809.19
  5029.0 1809.69  5039.6 1810.08  5046.1 1811.11  5051.7 1813.46  5089.9 1815.88
  5312.2 1819.46  5459.8 1821.30  5482.5 1821.06  5489.0 1821.61  5732.4 1825.64
#Mann=3,-1,0
  4603.6    0.05       0  5019.4    0.03       0  5029.0    0.05       0
Bank Sta=5019.4,5029
Exp/Cntr=0.3,0.1

Type RM Length L Ch R = 1,3661,435,435,435
BEGIN DESCRIPTION:
Deadman 34 5.0
END DESCRIPTION:
XS GIS Cut Line= 3
      1662455.00      6917238.01      1662555.00      6917638.00
      1663254.99      6918437.99
#Sta/Elev= 30
  4582.0 1834.05  4605.2 1832.63  4654.1 1827.87  4705.7 1824.55  4728.9 1822.32
  4736.6 1820.90  4777.8 1816.22  4839.7 1810.45  4852.6 1810.20  4870.6 1811.45
  4888.6 1811.05  4953.1 1811.36  4997.6 1810.11  5001.4 1809.34  5015.7 1808.20
  5017.4 1807.11  5017.9 1806.61  5026.7 1806.61  5027.2 1807.11  5036.5 1809.79
  5050.8 1810.92  5058.4 1812.71  5093.5 1813.83  5220.7 1815.69  5553.8 1819.23
  5618.4 1821.09  5710.4 1822.74  5724.7 1823.49  5837.6 1825.21  6057.3 1831.20
#Mann=3,-1,0
  4582.0    0.05       0  5017.4    0.03       0  5027.2    0.05       0
Bank Sta=5017.4,5027.2
Exp/Cntr=0.3,0.1

Type RM Length L Ch R = 1,3226,439,439,439
BEGIN DESCRIPTION:
Deadman 34 4.0
END DESCRIPTION:
XS GIS Cut Line= 3
      1662060.49      6917245.76      1662205.00      6917838.00
      1662405.02      6918388.04
#Sta/Elev= 30
  4390.6 1830.65  4413.5 1829.59  4429.8 1827.84  4435.0 1828.08  4513.2 1819.89
  4518.3 1820.00  4547.3 1817.53  4554.9 1816.16  4560.0 1816.31  4596.5 1813.76
  4638.2 1812.03  4712.0 1810.05  4815.2 1810.12  4893.4 1808.59  4928.2 1809.44
  4959.0 1809.36  4969.3 1808.87  4989.9 1806.09  5010.6 1806.03  5011.1 1805.53
  5020.0 1805.53  5020.5 1806.03  5085.3 1809.63  5107.3 1811.77  5138.5 1813.18
  5341.4 1816.83  5404.6 1817.11  5427.8 1818.12  5453.1 1818.09  5585.5 1821.44
#Mann=3,-1,0
  4390.6    0.05       0  5010.6    0.03       0  5020.5    0.05       0
Bank Sta=5010.6,5020.5
Exp/Cntr=0.3,0.1

Type RM Length L Ch R = 1,2787,469,469,469
BEGIN DESCRIPTION:
Deadman 34 3.0
END DESCRIPTION:
XS GIS Cut Line= 3
      1661768.09      6917378.95      1661805.00      6917938.00
      1661955.00      6918438.02
#Sta/Elev= 30
  4440.1 1813.58  4466.6 1811.22  4471.6 1811.74  4489.3 1810.41  4519.3 1809.22
  4617.7 1807.87  4699.7 1807.98  4729.8 1806.80  4749.8 1804.78  4759.8 1804.47
  4850.0 1807.16  4900.2 1806.74  4960.3 1807.81  4980.3 1807.29  4997.9 1804.56
  5005.8 1804.17  5006.3 1803.67  5015.3 1803.67  5015.8 1804.17  5031.7 1805.07
  5055.2 1805.36  5094.3 1809.07  5121.3 1810.36  5126.5 1809.94  5154.4 1811.43
  5187.4 1812.11  5192.6 1811.65  5209.2 1811.92  5240.5 1813.52  5522.4 1819.69
#Mann=3,-1,0
  4440.1    0.05       0  5005.8    0.03       0  5015.8    0.05       0
Bank Sta=5005.8,5015.8
Exp/Cntr=0.3,0.1

Type RM Length L Ch R = 1,2318,132,132,132
BEGIN DESCRIPTION:
Deadman 34 2.0
END DESCRIPTION:
XS GIS Cut Line= 3
      1661609.21      6917509.20      1661355.00      6917888.00
      1661174.91      6918197.64
#Sta/Elev= 30
  4543.3 1807.18  4638.2 1806.34  4667.9 1805.31  4688.9 1804.06  4746.6 1804.02
  4760.9 1803.51  4797.0 1804.07  4869.0 1803.86  4935.0 1804.78  4941.0 1804.36
  4963.4 1804.26  4977.0 1803.23  5002.4 1802.38  5013.1 1801.35  5034.8 1801.51
  5035.3 1801.01  5044.4 1801.01  5044.9 1801.51  5050.4 1804.20  5057.3 1806.09
  5071.9 1806.72  5167.9 1807.69  5173.7 1807.35  5196.2 1807.66  5210.9 1807.37
  5226.7 1808.20  5242.4 1807.43  5306.9 1808.14  5335.0 1807.45  5357.7 1808.23
#Mann=3,-1,0
  4543.3    0.05       0  5034.8    0.03       0  5044.9    0.05       0
Bank Sta=5034.8,5044.9
Exp/Cntr=0.3,0.1

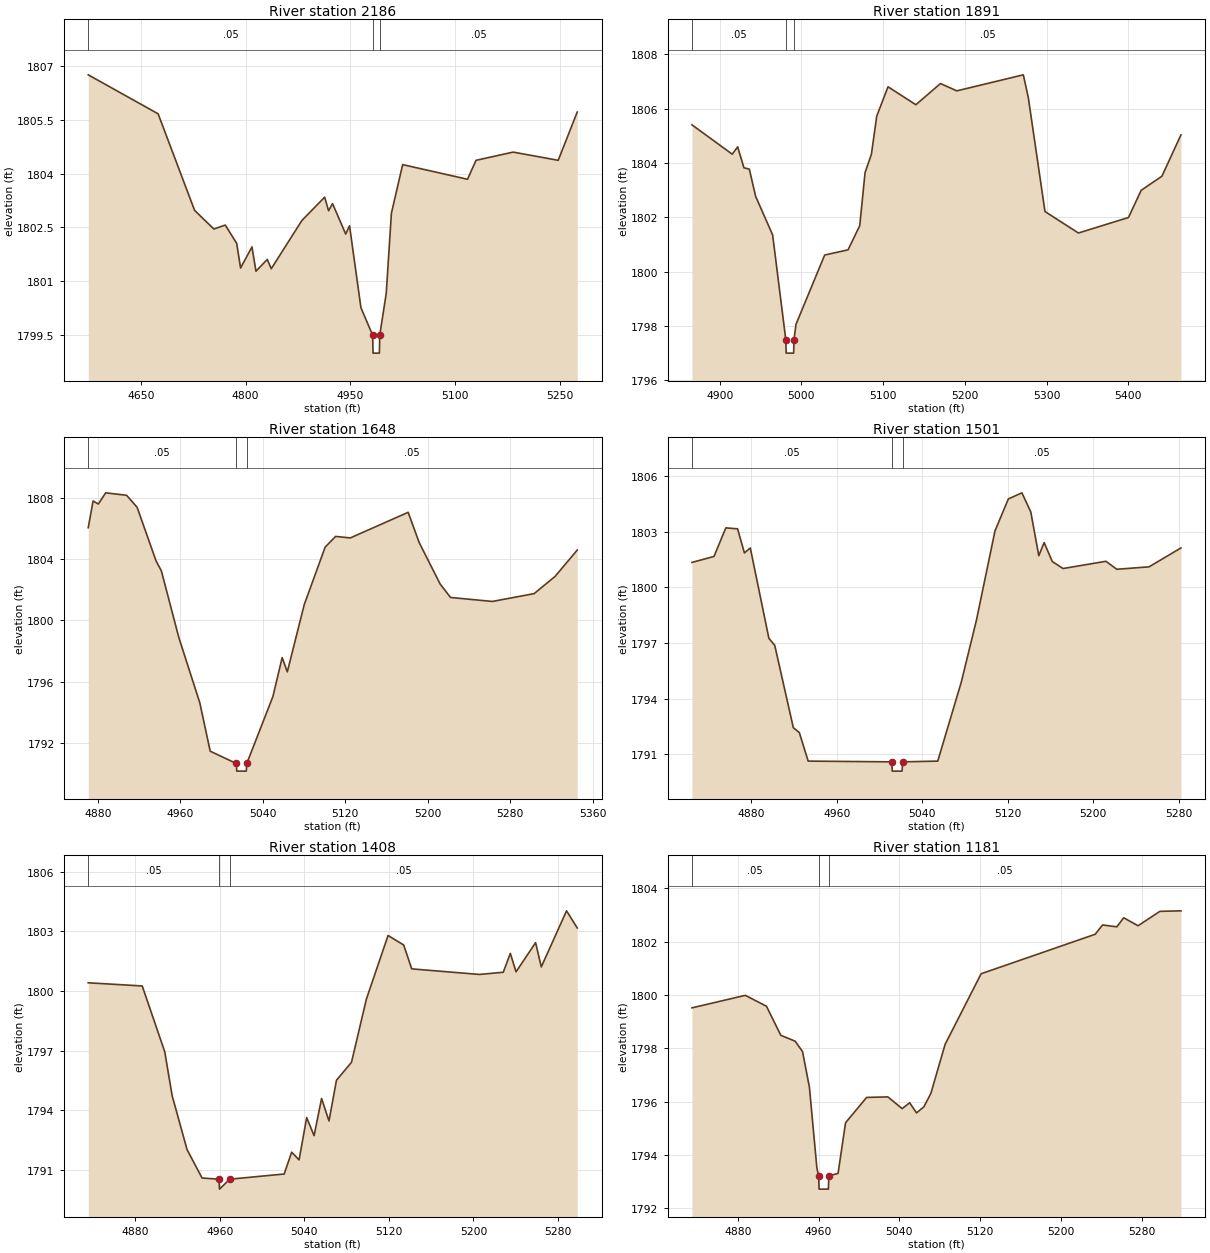
Type RM Length L Ch R = 1,2186,295,295,295
BEGIN DESCRIPTION:
Mapping XS 17fbcbea
END DESCRIPTION:
XS GIS Cut Line= 3
      1661492.42      6917449.81      1661322.04      6917767.85
      1661010.78      6917901.89
#Sta/Elev= 30
  4574.8 1806.76  4674.8 1805.67  4727.0 1802.97  4754.6 1802.45  4770.9 1802.56
  4787.2 1802.05  4792.8 1801.36  4809.1 1801.95  4814.8 1801.27  4831.0 1801.60
  4836.7 1801.34  4880.6 1802.69  4913.1 1803.34  4918.7 1802.96  4924.4 1803.16
  4943.2 1802.31  4948.7 1802.54  4965.0 1800.25  4981.8 1799.48  4982.3 1798.98
  4991.4 1798.98  4991.9 1799.48  5001.2 1800.65  5008.6 1802.89  5024.7 1804.25
  5117.5 1803.84  5129.7 1804.37  5182.8 1804.60  5247.3 1804.37  5274.5 1805.72
#Mann=3,-1,0
  4574.8    0.05       0  4981.8    0.03       0  4991.9    0.05       0
Bank Sta=4981.8,4991.9
Exp/Cntr=0.3,0.1

Type RM Length L Ch R = 1,1891,243,243,243
BEGIN DESCRIPTION:
Mapping XS 78c9764b
END DESCRIPTION:
XS GIS Cut Line= 4
      1661312.96      6917406.64      1661155.48      6917592.27
      1661013.95      6917602.32      1660969.97      6917810.82
#Sta/Elev= 30
  4866.1 1805.40  4915.4 1804.32  4922.0 1804.59  4929.7 1803.82  4936.3 1803.77
  4944.0 1802.77  4964.8 1801.35  4980.9 1797.50  4981.4 1797.00  4990.5 1797.00
  4991.0 1797.50  4993.4 1798.06  5028.5 1800.61  5057.1 1800.80  5071.4 1801.69
  5077.9 1803.64  5085.7 1804.32  5092.2 1805.72  5106.0 1806.80  5140.1 1806.14
  5170.2 1806.92  5190.2 1806.65  5271.6 1807.24  5277.7 1806.40  5298.1 1802.21
  5339.0 1801.42  5400.3 1801.99  5415.8 1802.99  5441.2 1803.51  5464.5 1805.03
#Mann=3,-1,0
  4866.1    0.05       0  4980.9    0.03       0  4991.0    0.05       0
Bank Sta=4980.9,4991
Exp/Cntr=0.3,0.1

Type RM Length L Ch R = 1,1648,147,147,147
BEGIN DESCRIPTION:
Mapping XS 13aaa039
END DESCRIPTION:
XS GIS Cut Line= 2
      1661031.26      6917311.28      1660954.02      6917779.25
#Sta/Elev= 30
  4870.7 1806.05  4875.4 1807.79  4880.5 1807.59  4887.6 1808.32  4907.9 1808.16
  4918.1 1807.38  4936.5 1803.88  4941.6 1803.24  4958.6 1798.88  4978.9 1794.64
  4989.0 1791.48  5014.3 1790.68  5014.8 1790.18  5024.0 1790.18  5024.5 1790.68
  5049.8 1795.04  5058.8 1797.58  5063.8 1796.65  5080.2 1801.03  5100.5 1804.78
  5110.6 1805.48  5124.9 1805.38  5181.0 1807.05  5191.7 1805.08  5212.0 1802.38
  5222.1 1801.50  5262.7 1801.24  5303.2 1801.75  5323.5 1802.87  5345.0 1804.59
#Mann=3,-1,0
  4870.7    0.05       0  5014.3    0.03       0  5024.5    0.05       0
Bank Sta=5014.3,5024.5
Exp/Cntr=0.3,0.1

Type RM Length L Ch R = 1,1501,93,93,93
BEGIN DESCRIPTION:
Mapping XS 7b4b27e9
END DESCRIPTION:
XS GIS Cut Line= 3
      1660798.94      6917309.28      1660927.54      6917586.54
      1660944.90      6917737.71
#Sta/Elev= 30
  4824.5 1801.35  4845.1 1801.67  4856.2 1803.21  4867.2 1803.16  4873.6 1801.86
  4879.1 1802.13  4896.5 1797.26  4902.0 1796.88  4919.4 1792.44  4925.0 1792.18
  4933.3 1790.64  5011.5 1790.60  5012.0 1790.10  5021.2 1790.10  5021.7 1790.60
  5054.6 1790.64  5076.6 1794.89  5090.8 1798.23  5108.2 1803.05  5120.7 1804.77
  5133.4 1805.10  5141.7 1804.07  5149.2 1801.71  5154.2 1802.42  5161.8 1801.40
  5171.9 1801.02  5212.1 1801.41  5222.2 1800.98  5252.4 1801.11  5282.3 1802.13
#Mann=3,-1,0
  4824.5    0.05       0  5011.5    0.05       0  5021.7    0.05       0
Bank Sta=5011.5,5021.7
Exp/Cntr=0.3,0.1

Type RM Length L Ch R = 1,1408,227,227,227
BEGIN DESCRIPTION:
Mapping XS 006730f0
END DESCRIPTION:
XS GIS Cut Line= 3
      1660674.58      6917386.17      1660877.12      6917591.95
      1660943.73      6917752.66
#Sta/Elev= 30
  4835.5 1800.41  4886.6 1800.25  4907.9 1796.94  4914.9 1794.73  4929.0 1792.02
  4943.2 1790.59  4959.2 1790.53  4959.7 1790.03  4969.4 1790.53  5020.9 1790.79
  5028.0 1791.89  5035.0 1791.50  5042.2 1793.63  5049.2 1792.72  5056.3 1794.59
  5063.3 1793.46  5070.4 1795.51  5084.6 1796.41  5098.7 1799.59  5119.2 1802.79
  5134.0 1802.31  5141.6 1801.11  5205.6 1800.83  5228.2 1800.94  5234.9 1801.89
  5240.3 1800.96  5258.8 1802.43  5264.2 1801.21  5288.1 1804.03  5298.2 1803.17
#Mann=3,-1,0
  4835.5    0.05       0  4959.2    0.05       0  4969.4    0.05       0
Bank Sta=4959.2,4969.4
Exp/Cntr=0.3,0.1

Type RM Length L Ch R = 1,1181,269,269,269
BEGIN DESCRIPTION:
Mapping XS c940f8c5
END DESCRIPTION:
XS GIS Cut Line= 2
      1660533.28      6917565.22      1660889.06      6917893.81
#Sta/Elev= 30
  4834.6 1799.52  4887.4 1799.99  4908.4 1799.58  4922.6 1798.49  4936.8 1798.27
  4944.1 1797.88  4950.9 1796.55  4958.3 1793.52  4960.0 1793.22  4960.5 1792.72
  4969.7 1792.72  4970.2 1793.22  4979.3 1793.31  4986.7 1795.21  5007.6 1796.16
  5028.6 1796.18  5042.8 1795.74  5050.2 1795.96  5057.0 1795.58  5064.3 1795.81
  5071.2 1796.31  5085.3 1798.15  5121.0 1800.80  5233.9 1802.28  5241.3 1802.63
  5255.4 1802.56  5262.2 1802.90  5276.4 1802.60  5298.0 1803.14  5318.9 1803.16
#Mann=3,-1,0
  4834.6    0.05       0  4960.0    0.03       0  4970.2    0.05       0
Bank Sta=4960,4970.2
Exp/Cntr=0.3,0.1

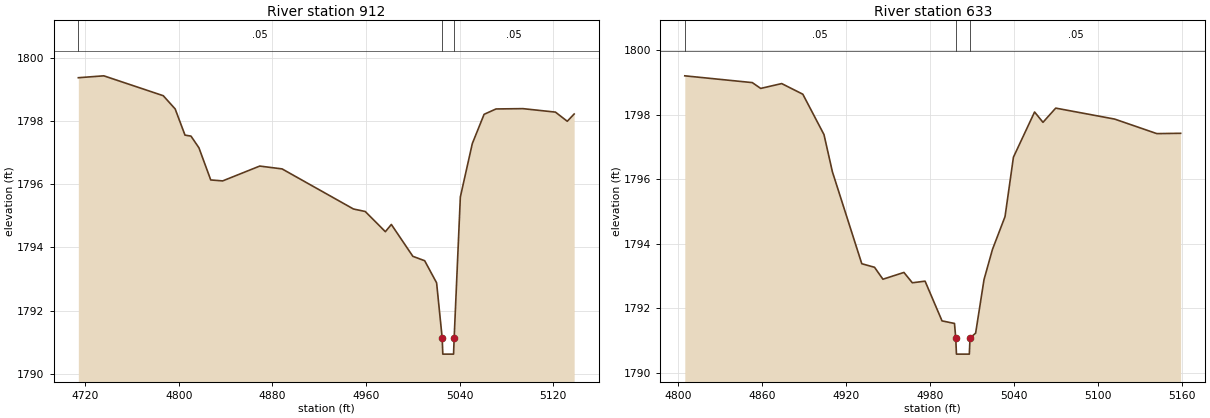
Type RM Length L Ch R = 1,912,279,279,279
BEGIN DESCRIPTION:
Mapping XS da16489c
END DESCRIPTION:
XS GIS Cut Line= 2
      1660513.32      6917606.53      1660588.15      6918023.78
#Sta/Elev= 30
  4714.0 1799.38  4735.8 1799.44  4786.6 1798.81  4796.8 1798.39  4805.2 1797.56
  4810.3 1797.53  4817.1 1797.16  4827.2 1796.14  4837.4 1796.11  4869.1 1796.58
  4888.2 1796.49  4949.2 1795.22  4959.3 1795.14  4976.5 1794.50  4981.6 1794.73
  5000.0 1793.72  5010.1 1793.58  5020.3 1792.88  5025.1 1791.12  5025.6 1790.62
  5034.8 1790.62  5035.3 1791.12  5040.6 1795.60  5050.8 1797.29  5060.9 1798.22
  5071.1 1798.39  5094.1 1798.40  5121.9 1798.29  5132.0 1798.00  5137.9 1798.23
#Mann=3,-1,0
  4714.0    0.05       0  5025.1    0.03       0  5035.3    0.05       0
Bank Sta=5025.1,5035.3
Exp/Cntr=0.3,0.1

Type RM Length L Ch R = 1,633,165,165,165
BEGIN DESCRIPTION:
Mapping XS a33e2e7d
END DESCRIPTION:
XS GIS Cut Line= 2
      1660467.88      6917574.76      1660272.51      6917870.09
#Sta/Elev= 30
  4804.8 1799.20  4853.0 1798.99  4859.0 1798.81  4874.0 1798.96  4889.1 1798.63
  4904.2 1797.38  4910.2 1796.23  4931.2 1793.38  4940.3 1793.27  4946.3 1792.90
  4961.3 1793.11  4967.3 1792.79  4976.4 1792.84  4988.5 1791.61  4997.4 1791.53
  4998.3 1791.08  4998.8 1790.58  5008.0 1790.58  5008.5 1791.08  5012.5 1791.23
  5018.5 1792.89  5024.5 1793.82  5033.5 1794.84  5039.5 1796.68  5054.6 1798.08
  5060.6 1797.76  5069.7 1798.20  5111.8 1797.86  5141.9 1797.41  5158.9 1797.42
#Mann=3,-1,0
  4804.8    0.05       0  4998.3    0.03       0  5008.5    0.05       0
Bank Sta=4998.3,5008.5
Exp/Cntr=0.3,0.1