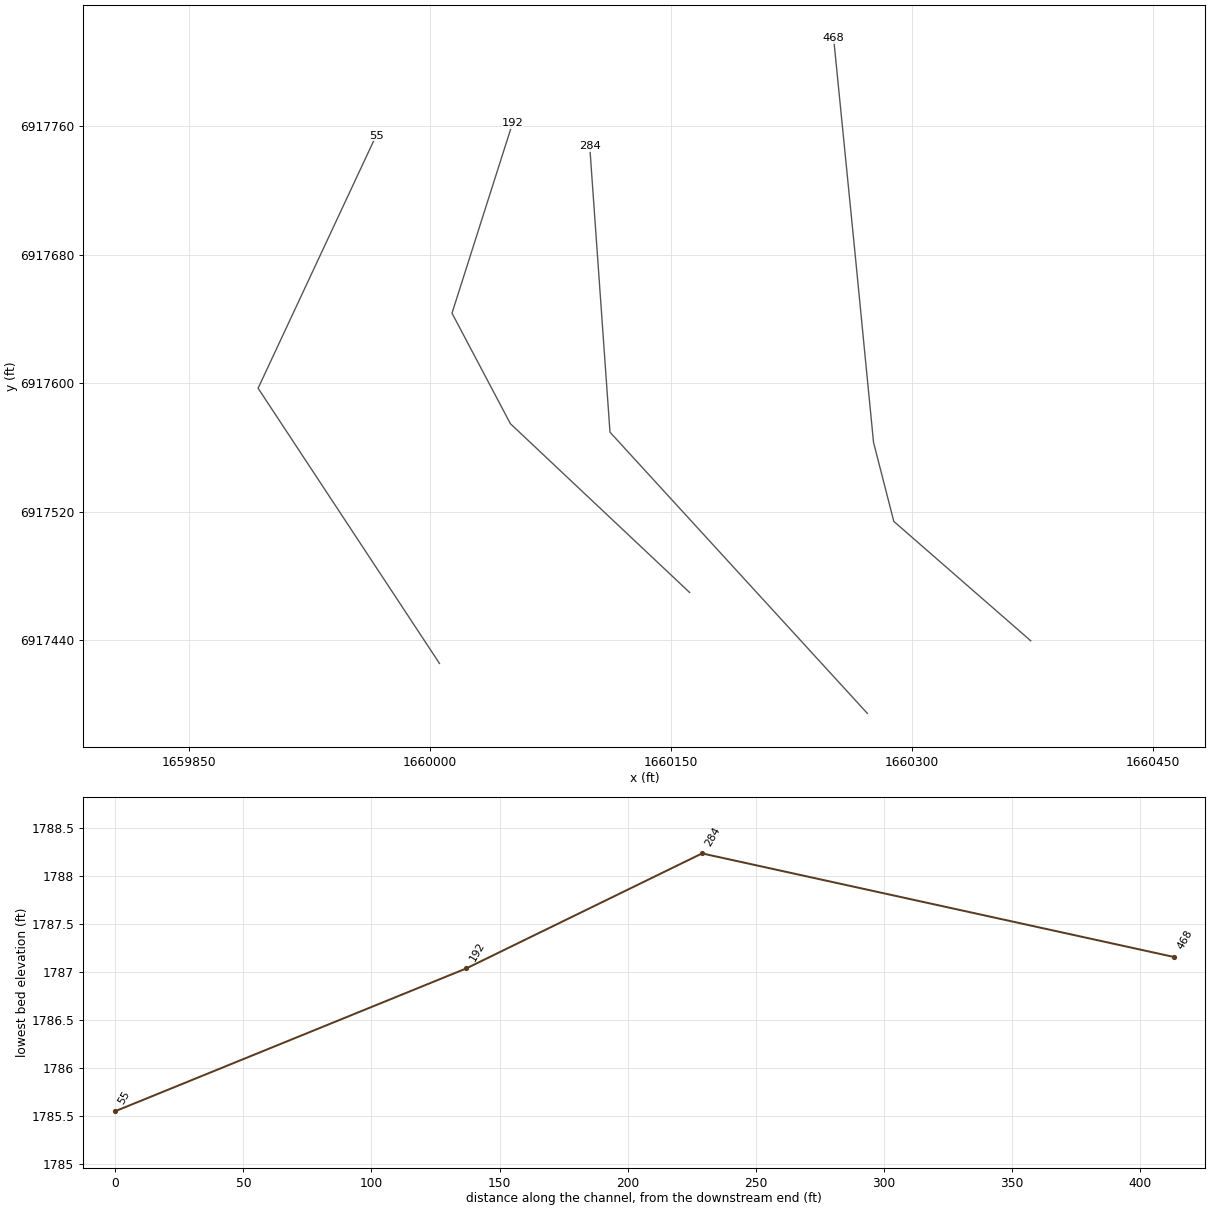
HEC-RAS study Deadman 34.prj: Deadman 34 Base Level Engineering

--- Deadman 34.g01 (geometry) --- (continued)

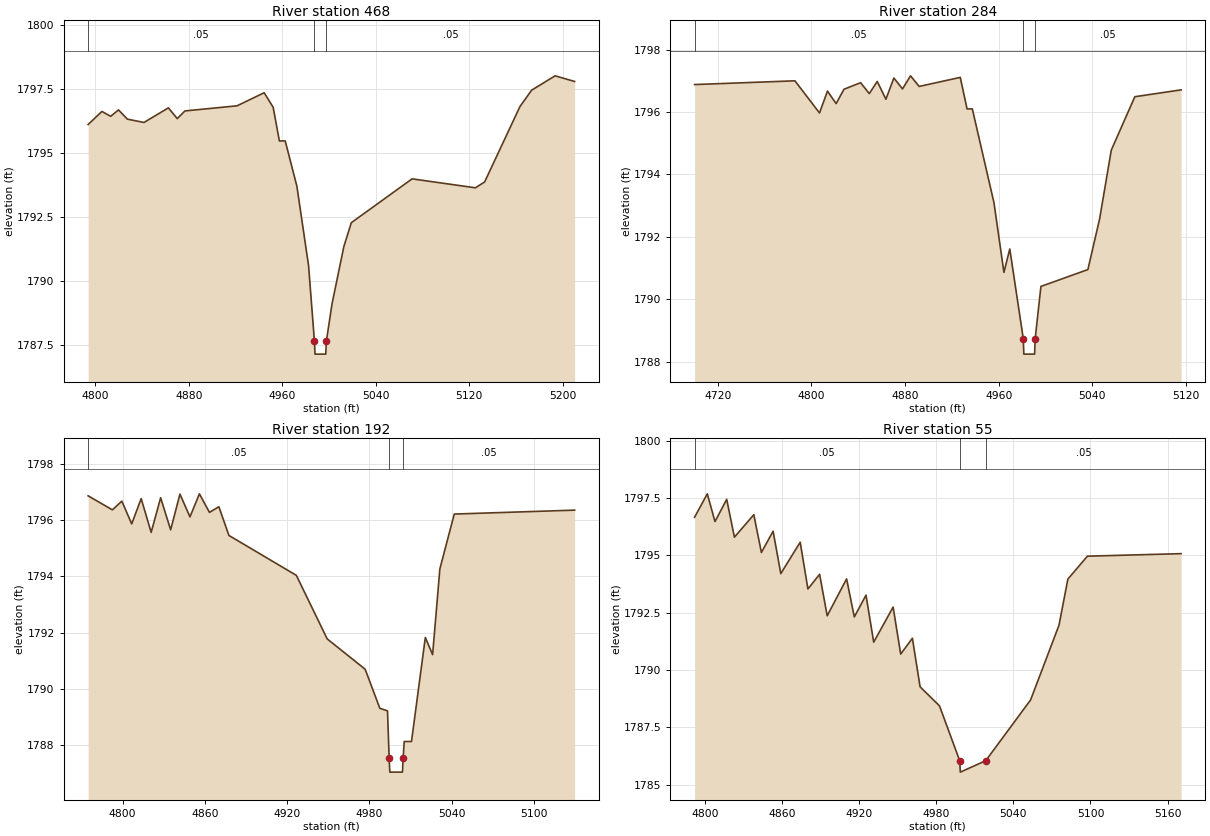
Type RM Length L Ch R = 1,468,184,184,184
BEGIN DESCRIPTION:
Mapping XS 8b23426a
END DESCRIPTION:
XS GIS Cut Line= 5
      1660373.93      6917439.74      1660288.73      6917514.04
      1660276.12      6917563.22      1660264.77      6917679.26
      1660251.30      6917814.58
#Sta/Elev= 30
  4793.8 1796.12  4805.6 1796.63  4813.1 1796.44  4819.8 1796.69  4827.4 1796.33
  4841.6 1796.20  4862.5 1796.77  4870.1 1796.35  4876.7 1796.65  4921.3 1796.85
  4944.5 1797.36  4952.2 1796.79  4957.5 1795.48  4962.5 1795.48  4972.5 1793.71
  4982.5 1790.61  4987.5 1787.66  4988.0 1787.16  4997.2 1787.16  4997.7 1787.66
  5002.6 1789.13  5012.7 1791.36  5019.1 1792.29  5071.1 1794.00  5125.3 1793.65
  5133.2 1793.88  5163.4 1796.82  5173.4 1797.46  5193.5 1798.02  5210.2 1797.80
#Mann=3,-1,0
  4793.8    0.05       0  4987.5    0.03       0  4997.7    0.05       0
Bank Sta=4987.5,4997.7
Exp/Cntr=0.3,0.1

Type RM Length L Ch R = 1,284,92,92,92
BEGIN DESCRIPTION:
Mapping XS 2525cba2
END DESCRIPTION:
XS GIS Cut Line= 4
      1660272.28      6917394.58      1660180.26      6917495.12
      1660112.15      6917569.53      1660099.54      6917747.42
#Sta/Elev= 30
  4700.3 1796.88  4786.0 1797.00  4807.0 1795.97  4813.8 1796.67  4821.2 1796.27
  4827.9 1796.73  4842.1 1796.94  4849.5 1796.59  4856.3 1796.98  4863.7 1796.41
  4870.5 1797.09  4877.9 1796.74  4884.7 1797.16  4892.1 1796.82  4927.2 1797.11
  4933.0 1796.10  4937.5 1796.10  4956.0 1793.09  4964.5 1790.86  4969.5 1791.61
  4981.0 1788.74  4981.5 1788.24  4990.7 1788.24  4991.2 1788.74  4996.1 1790.41
  5036.2 1790.95  5046.2 1792.57  5056.2 1794.78  5076.3 1796.49  5115.8 1796.71
#Mann=3,-1,0
  4700.3    0.05       0  4981.0    0.03       0  4991.2    0.05       0
Bank Sta=4981,4991.2
Exp/Cntr=0.3,0.1

Type RM Length L Ch R = 1,192,137,137,137
BEGIN DESCRIPTION:
Mapping XS adebb0c8
END DESCRIPTION:
XS GIS Cut Line= 4
      1660161.71      6917469.78      1660050.17      6917574.83
      1660013.85      6917643.58      1660051.48      6917761.65
#Sta/Elev= 30
  4774.9 1796.87  4792.6 1796.37  4799.5 1796.68  4806.7 1795.87  4813.6 1796.77
  4820.9 1795.57  4827.8 1796.80  4835.1 1795.66  4841.9 1796.93  4849.2 1796.12
  4856.1 1796.94  4863.4 1796.28  4870.3 1796.48  4877.6 1795.46  4926.8 1794.04
  4949.3 1791.78  4977.0 1790.70  4987.7 1789.31  4993.3 1789.22  4994.5 1787.54
  4995.0 1787.04  5004.2 1787.04  5004.7 1787.54  5005.5 1788.13  5010.8 1788.13
  5020.9 1791.83  5026.2 1791.22  5031.5 1794.27  5042.0 1796.22  5129.8 1796.36
#Mann=3,-1,0
  4774.9    0.05       0  4994.5    0.05       0  5004.7    0.05       0
Bank Sta=4994.5,5004.7
Exp/Cntr=0.3,0.1

Type RM Length L Ch R = 1,55,0,0,0
BEGIN DESCRIPTION:
Deadman 34 1.0
END DESCRIPTION:
XS GIS Cut Line= 3
      1660006.06      6917425.65      1659893.21      6917596.88
      1659966.66      6917754.09
#Sta/Elev= 30
  4791.9 1796.67  4801.8 1797.69  4807.8 1796.48  4816.9 1797.45  4822.9 1795.80
  4838.0 1796.78  4843.9 1795.13  4853.0 1796.06  4859.0 1794.21  4874.1 1795.58
  4880.1 1793.54  4889.2 1794.18  4895.1 1792.37  4910.2 1793.98  4916.2 1792.32
  4925.3 1793.27  4931.3 1791.22  4946.4 1792.75  4952.3 1790.70  4961.4 1791.39
  4967.4 1789.27  4982.5 1788.44  4998.2 1786.05  4998.7 1785.55  5018.5 1786.05
  5053.4 1788.70  5075.5 1791.96  5082.4 1793.97  5097.6 1794.97  5170.5 1795.08
#Mann=3,-1,0
  4791.9    0.05       0  4998.2    0.03       0  5018.5    0.05       0
Bank Sta=4998.2,5018.5
Exp/Cntr=0.3,0.1

Chan Stop Cuts=-1