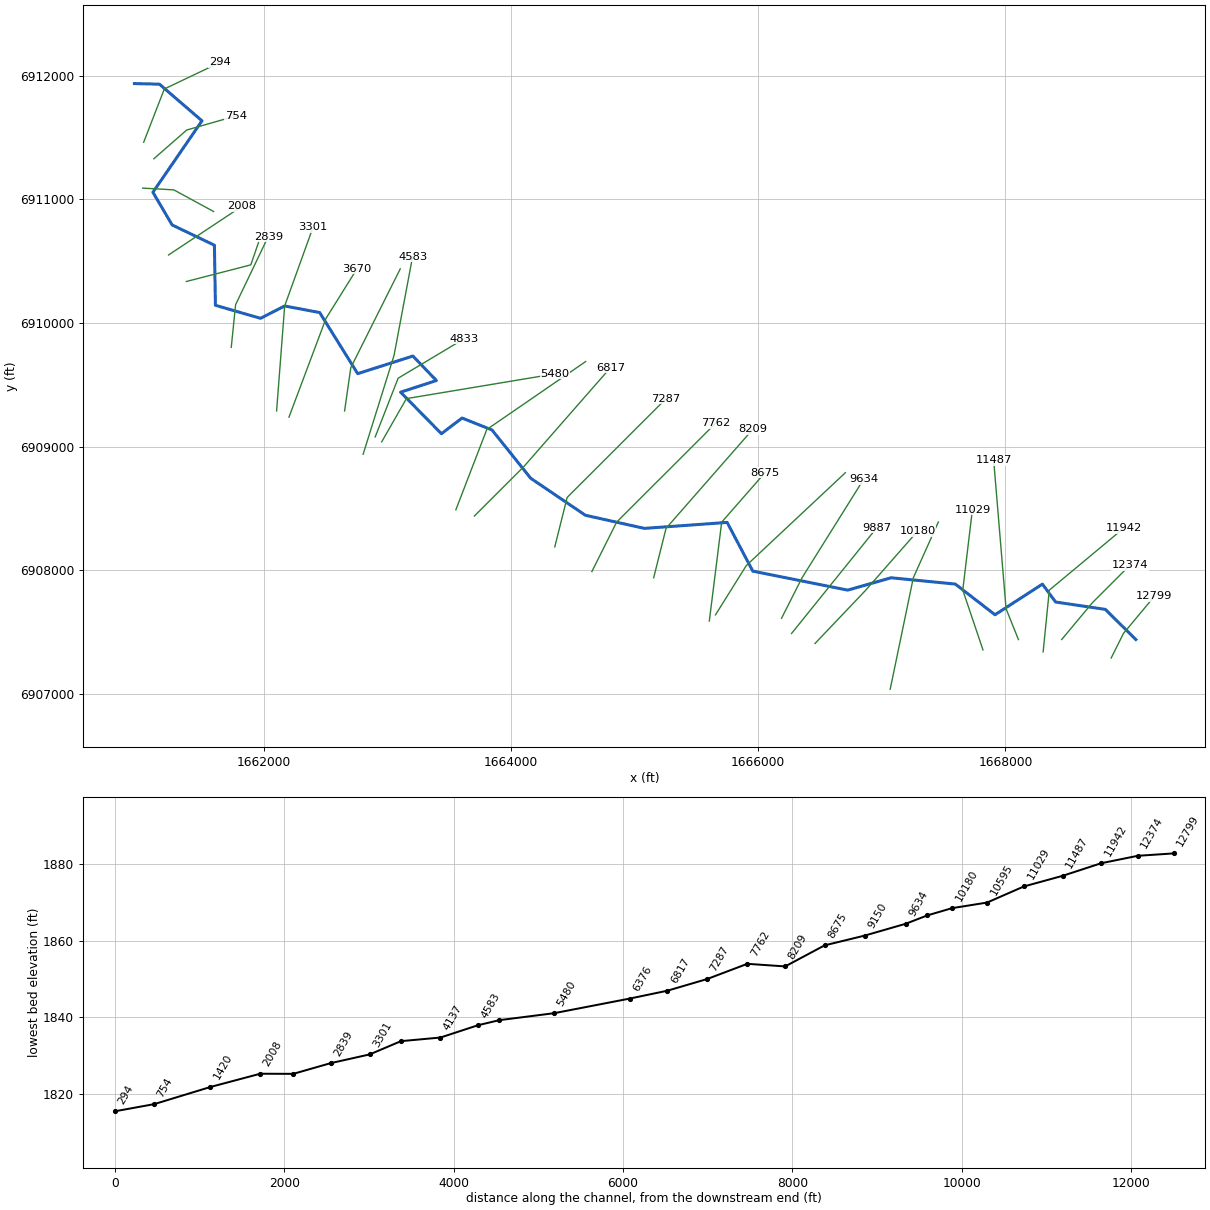
--- Deadman 35.prj (project) ---

Proj Title=Deadman 35 Base Level Engineering
Current Plan=p01
Default Exp/Contr=0.3,0.1
English Units
Geom File=g01
Flow File=f01
Plan File=p01
BEGIN DESCRIPTION:
Deadman 35
END DESCRIPTION:

--- Deadman 35.p01 (plan) ---

Plan Title=Multiple Run
Short Identifier=Multiple
Geom File=g01
Flow File=f01
Subcritical Flow
K Sum by GR= 0
Std Step Tol= 0.01
Critical Tol= 0.01
Num of Std Step Trials= 20
Max Error Tol= 0.3
Flow Tol Ratio= 0.001
Split Flow NTrial= 30
Split Flow Tol= 0.02
Split Flow Ratio= 0.02
Log Output Level= 0
Friction Slope Method= 1
Unsteady Friction Slope Method= 2
Unsteady Bridges Friction Slope Method= 1
Parabolic Critical Depth
Global Vel Dist=  1 , 1 , 1
Global Log Level= 0
CheckData=True
Encroach Param= -1, 0, 0, 0
BEGIN DESCRIPTION:
Multiple Run
END DESCRIPTION:

--- Deadman 35.f01 (steady flow) ---

Flow Title=Multiple
Number of Profiles=7
Profile Names=10-year,25-year,50-year,1pct_min,100-year,1pct_plu,500-year
River Rch & RM= Deadman 35,Reach-1,12799
     342     479     594     366     731    1458    1121
River Rch & RM= Deadman 35,Reach-1,4833
     378     532     661     408     814    1625    1253
Boundary for River Rch & Prof#=Deadman 35,Reach-1,1
Up Type=0
Dn Type=3
Dn Slope=0.005
Boundary for River Rch & Prof#=Deadman 35,Reach-1,2
Up Type=0
Dn Type=3
Dn Slope=0.005
Boundary for River Rch & Prof#=Deadman 35,Reach-1,3
Up Type=0
Dn Type=3
Dn Slope=0.005
Boundary for River Rch & Prof#=Deadman 35,Reach-1,4
Up Type=0
Dn Type=3
Dn Slope=0.005
Boundary for River Rch & Prof#=Deadman 35,Reach-1,5
Up Type=0
Dn Type=3
Dn Slope=0.005
Boundary for River Rch & Prof#=Deadman 35,Reach-1,6
Up Type=0
Dn Type=3
Dn Slope=0.005
Boundary for River Rch & Prof#=Deadman 35,Reach-1,7
Up Type=0
Dn Type=3
Dn Slope=0.005

--- Deadman 35.g01 (geometry) ---

Geom Title=Existing Conditions

River Reach=Deadman 35,Reach-1
Reach XY= 30
      1669055.00      6907438.00      1668807.84      6907682.17
      1668406.28      6907741.52      1668299.15      6907886.46
      1667915.69      6907638.54      1667594.57      6907886.95
      1667075.03      6907937.94      1666725.03      6907838.07
      1665956.52      6907991.74      1665749.16      6908385.95
      1665079.88      6908337.71      1664602.70      6908443.83
      1664160.44      6908743.19      1663846.66      6909134.84
      1663604.90      6909230.72      1663438.15      6909103.97
      1663107.94      6909440.01      1663397.52      6909534.35
      1663207.69      6909732.61      1662760.88      6909589.95
      1662453.54      6910084.46      1662170.22      6910137.75
      1661975.10      6910037.90      1661610.18      6910143.38
      1661601.93      6910629.70      1661260.44      6910793.25
      1661104.53      6911058.16      1661501.54      6911636.50
      1661157.53      6911932.98      1660955.00      6911938.00

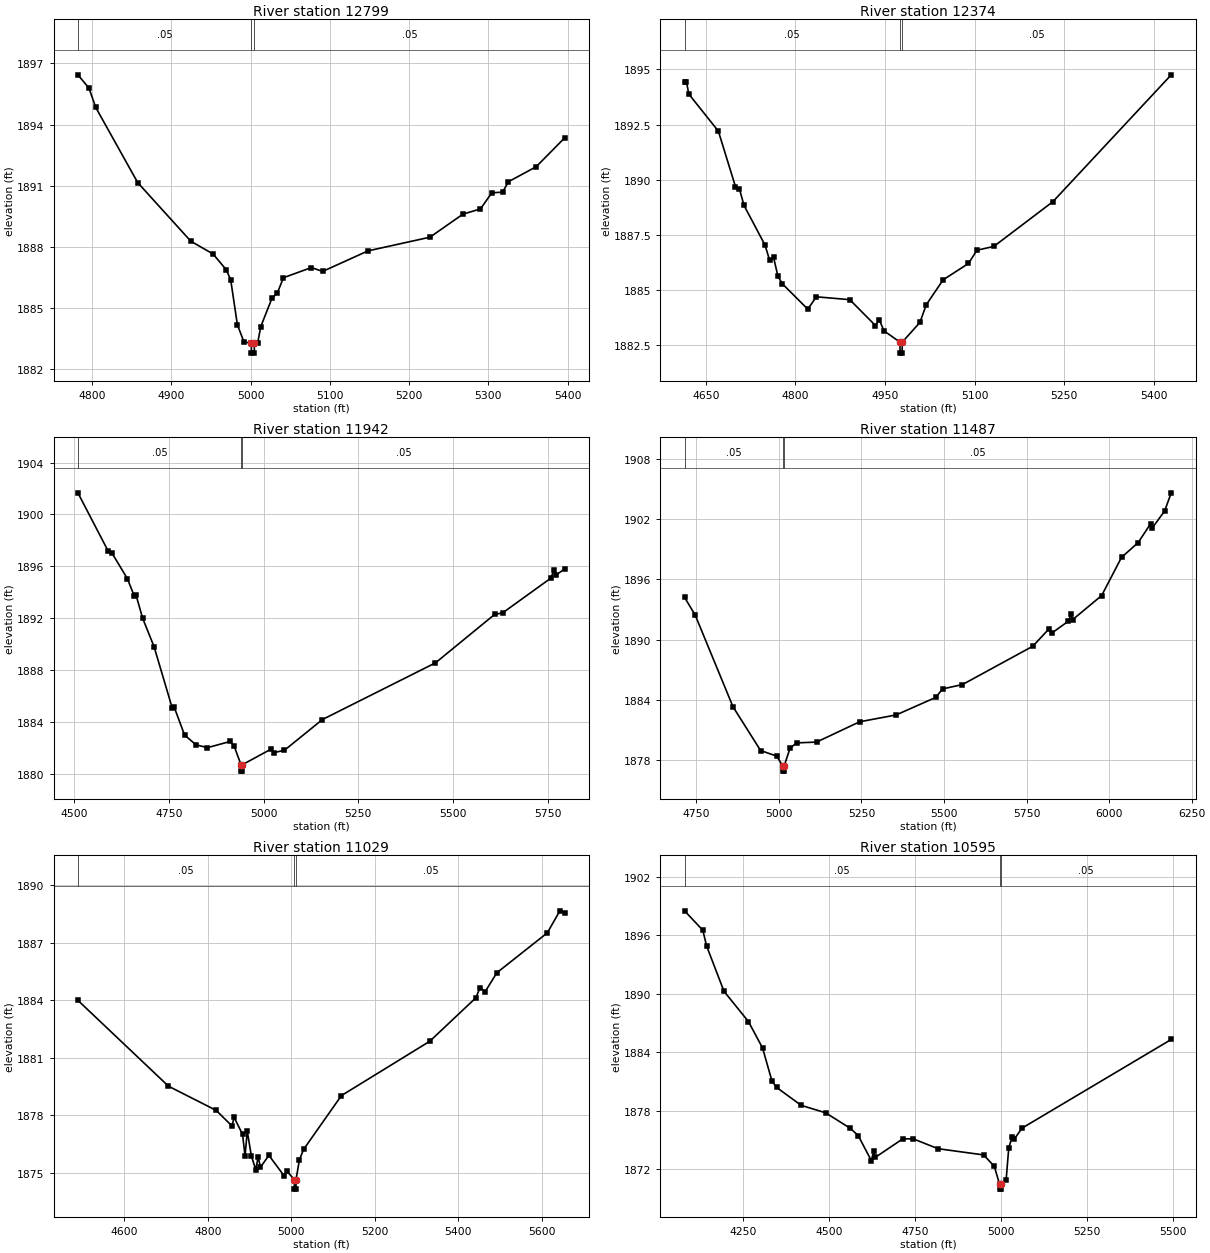
Type RM Length L Ch R = 1,12799,425,425,425
BEGIN DESCRIPTION:
Deadman 35 21.0
END DESCRIPTION:
XS GIS Cut Line= 3
      1668854.99      6907287.97      1668955.00      6907488.00
      1669205.03      6907788.04
#Sta/Elev= 30
  4782.0 1896.44  4796.0 1895.79  4804.4 1894.85  4857.5 1891.15  4924.6 1888.27
  4952.5 1887.65  4969.3 1886.87  4974.9 1886.37  4983.3 1884.17  4991.7 1883.32
  5000.8 1883.28  5001.1 1882.78  5004.6 1882.78  5004.8 1883.28  5008.9 1883.28
  5012.8 1884.08  5027.1 1885.49  5033.6 1885.72  5041.4 1886.48  5076.6 1886.98
  5090.9 1886.79  5148.2 1887.80  5226.3 1888.47  5267.9 1889.60  5290.1 1889.86
  5304.4 1890.65  5318.0 1890.68  5325.2 1891.19  5360.4 1891.93  5396.2 1893.34
#Mann=3,-1,0
  4782.0    0.05       0  5000.8    0.03       0  5004.8    0.05       0
Bank Sta=5000.8,5004.8
Exp/Cntr=0.3,0.1

Type RM Length L Ch R = 1,12374,432,432,432
BEGIN DESCRIPTION:
Deadman 35 20.0
END DESCRIPTION:
XS GIS Cut Line= 3
      1668455.03      6907438.04      1668705.00      6907738.00
      1669004.98      6908037.98
#Sta/Elev= 30
  4614.6 1894.43  4617.8 1894.43  4621.7 1893.88  4671.2 1892.20  4699.8 1889.69
  4706.3 1889.60  4714.1 1888.84  4749.3 1887.04  4757.1 1886.35  4763.6 1886.49
  4770.8 1885.64  4777.9 1885.30  4820.9 1884.14  4835.2 1884.70  4891.2 1884.57
  4934.1 1883.40  4940.6 1883.66  4948.4 1883.16  4975.1 1882.65  4975.3 1882.15
  4978.8 1882.15  4979.1 1882.65  5008.6 1883.54  5019.2 1884.34  5047.5 1885.47
  5089.9 1886.21  5104.1 1886.81  5132.3 1886.98  5231.3 1889.01  5429.3 1894.75
#Mann=3,-1,0
  4614.6    0.05       0  4975.1    0.03       0  4979.1    0.05       0
Bank Sta=4975.1,4979.1
Exp/Cntr=0.3,0.1

Type RM Length L Ch R = 1,11942,455,455,455
BEGIN DESCRIPTION:
Deadman 35 19.0
END DESCRIPTION:
XS GIS Cut Line= 3
      1668305.00      6907338.03      1668355.00      6907838.00
      1668955.01      6908338.01
#Sta/Elev= 30
  4510.3 1901.67  4590.7 1897.15  4600.7 1897.00  4640.9 1895.05  4658.5 1893.75
  4663.5 1893.80  4681.1 1892.00  4711.3 1889.80  4759.0 1885.09  4764.0 1885.17
  4791.7 1882.99  4821.8 1882.24  4852.0 1882.02  4912.3 1882.50  4922.3 1882.15
  4940.4 1880.71  4940.7 1880.21  4944.2 1880.21  4944.4 1880.71  5019.9 1881.91
  5026.4 1881.63  5055.1 1881.82  5155.3 1884.19  5453.4 1888.56  5609.6 1892.30
  5630.4 1892.41  5758.0 1895.10  5765.8 1895.75  5772.3 1895.35  5793.8 1895.80
#Mann=3,-1,0
  4510.3    0.05       0  4940.4    0.03       0  4944.4    0.05       0
Bank Sta=4940.4,4944.4
Exp/Cntr=0.3,0.1

Type RM Length L Ch R = 1,11487,458,458,458
BEGIN DESCRIPTION:
Deadman 35 18.0
END DESCRIPTION:
XS GIS Cut Line= 3
      1668104.99      6907438.03      1668005.00      6907688.00
      1667905.00      6908888.01
#Sta/Elev= 30
  4714.6 1894.21  4746.9 1892.44  4861.3 1883.32  4944.8 1878.97  4993.9 1878.41
  5011.8 1877.42  5012.1 1876.92  5015.8 1876.92  5016.1 1877.42  5034.0 1879.21
  5054.1 1879.73  5114.3 1879.81  5244.7 1881.83  5355.1 1882.51  5475.5 1884.26
  5495.6 1885.10  5555.8 1885.53  5769.0 1889.35  5816.7 1891.03  5826.7 1890.66
  5876.9 1891.85  5884.4 1892.51  5889.5 1891.99  5977.3 1894.39  6037.5 1898.19
  6087.6 1899.65  6125.3 1901.52  6130.3 1901.10  6167.9 1902.80  6188.0 1904.61
#Mann=3,-1,0
  4714.6    0.05       0  5011.8    0.03       0  5016.1    0.05       0
Bank Sta=5011.8,5016.1
Exp/Cntr=0.3,0.1

Type RM Length L Ch R = 1,11029,434,434,434
BEGIN DESCRIPTION:
Deadman 35 17.0
END DESCRIPTION:
XS GIS Cut Line= 3
      1667818.38      6907354.02      1667655.00      6907838.00
      1667732.89      6908489.15
#Sta/Elev= 30
  4488.7 1883.99  4705.9 1879.51  4820.1 1878.25  4857.9 1877.44  4863.2 1877.88
  4883.4 1877.00  4889.4 1875.87  4894.7 1877.16  4904.5 1875.88  4915.1 1875.15
  4920.9 1875.84  4926.1 1875.28  4946.7 1875.90  4983.8 1874.81  4989.1 1875.09
  5007.4 1874.64  5007.7 1874.14  5011.4 1874.14  5011.7 1874.64  5019.7 1875.67
  5029.7 1876.21  5120.4 1879.02  5331.9 1881.85  5442.6 1884.12  5452.7 1884.65
  5465.2 1884.45  5493.0 1885.43  5613.9 1887.51  5644.1 1888.66  5655.3 1888.55
#Mann=3,-1,0
  4488.7    0.05       0  5007.4    0.03       0  5011.7    0.05       0
Bank Sta=5007.4,5011.7
Exp/Cntr=0.3,0.1

Type RM Length L Ch R = 1,10595,415,415,415
BEGIN DESCRIPTION:
Deadman 35 16.0
END DESCRIPTION:
XS GIS Cut Line= 3
      1667067.96      6907035.83      1667255.00      6907938.00
      1667457.43      6908389.43
#Sta/Elev= 30
  4079.1 1898.50  4132.4 1896.50  4143.0 1894.92  4193.7 1890.25  4265.1 1887.13
  4306.0 1884.43  4333.5 1881.03  4346.8 1880.38  4418.3 1878.54  4489.8 1877.77
  4561.3 1876.18  4584.3 1875.44  4622.6 1872.86  4629.3 1873.83  4634.5 1873.21
  4714.5 1875.11  4745.1 1875.09  4816.6 1874.09  4949.4 1873.45  4980.5 1872.27
  4995.7 1870.44  4996.0 1869.94  4999.8 1869.94  5000.1 1870.44  5014.8 1870.89
  5022.4 1874.17  5032.5 1875.34  5038.0 1875.05  5061.1 1876.20  5495.2 1885.30
#Mann=3,-1,0
  4079.1    0.05       0  4995.7    0.03       0  5000.1    0.05       0
Bank Sta=4995.7,5000.1
Exp/Cntr=0.3,0.1

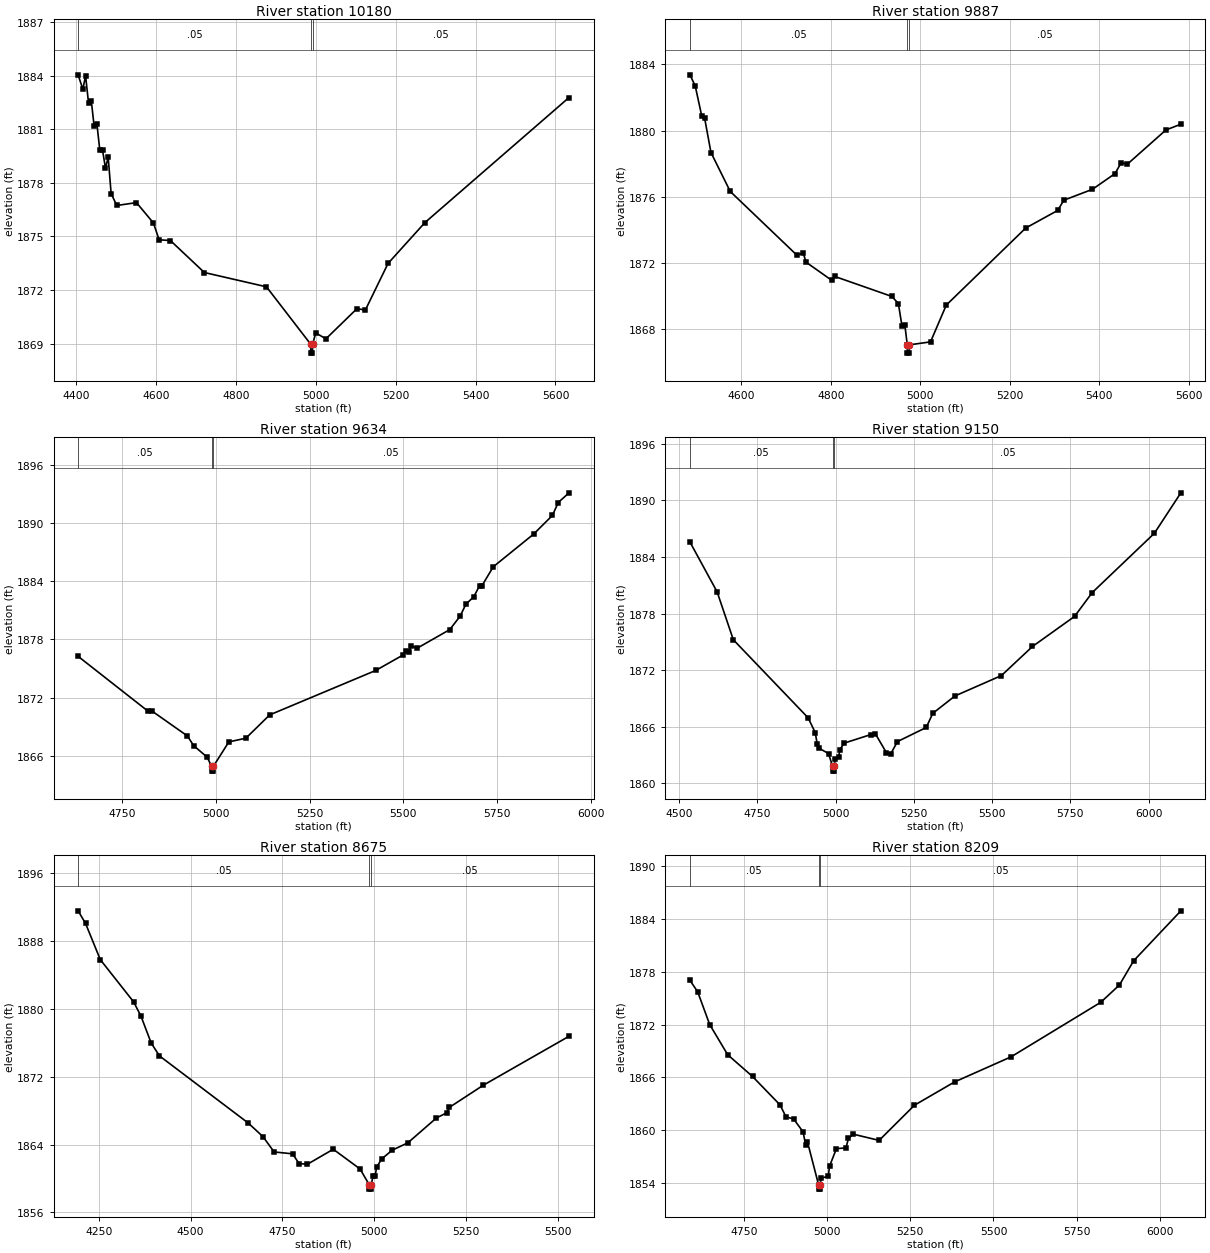
Type RM Length L Ch R = 1,10180,293,293,293
BEGIN DESCRIPTION:
Deadman 35 15.0
END DESCRIPTION:
XS GIS Cut Line= 3
      1666460.01      6907406.25      1666870.18      6907837.56
      1667288.41      6908313.91
#Sta/Elev= 30
  4404.8 1884.04  4416.7 1883.24  4423.6 1883.98  4430.9 1882.47  4437.8 1882.60
  4445.0 1881.16  4451.9 1881.30  4459.2 1879.82  4466.1 1879.81  4473.3 1878.83
  4480.2 1879.42  4487.5 1877.40  4501.6 1876.73  4551.0 1876.89  4593.5 1875.75
  4607.6 1874.81  4635.9 1874.77  4720.9 1872.98  4876.4 1872.18  4987.1 1868.97
  4987.4 1868.47  4991.5 1868.47  4991.9 1868.97  4999.9 1869.60  5025.3 1869.27
  5103.1 1870.96  5124.0 1870.88  5180.9 1873.49  5273.0 1875.77  5633.9 1882.77
#Mann=3,-1,0
  4404.8    0.05       0  4987.1    0.03       0  4991.9    0.05       0
Bank Sta=4987.1,4991.9
Exp/Cntr=0.3,0.1

Type RM Length L Ch R = 1,9887,253,253,253
BEGIN DESCRIPTION:
Mapping XS baabebb6
END DESCRIPTION:
XS GIS Cut Line= 2
      1666270.06      6907487.02      1666958.74      6908341.94
#Sta/Elev= 30
  4484.9 1883.37  4496.7 1882.70  4511.1 1880.91  4517.5 1880.79  4531.9 1878.68
  4575.0 1876.33  4723.8 1872.49  4738.2 1872.61  4744.6 1872.06  4802.2 1870.96
  4808.6 1871.20  4936.6 1869.99  4951.0 1869.56  4958.9 1868.23  4965.4 1868.28
  4970.9 1867.07  4971.2 1866.57  4975.4 1866.57  4975.8 1867.07  5022.9 1867.25
  5058.1 1869.47  5235.7 1874.12  5307.6 1875.19  5320.8 1875.80  5385.0 1876.46
  5435.6 1877.41  5449.2 1878.07  5462.8 1877.97  5549.2 1880.04  5582.7 1880.39
#Mann=3,-1,0
  4484.9    0.05       0  4970.9    0.03       0  4975.8    0.05       0
Bank Sta=4970.9,4975.8
Exp/Cntr=0.3,0.1

Type RM Length L Ch R = 1,9634,484,484,484
BEGIN DESCRIPTION:
Deadman 35 14.0
END DESCRIPTION:
XS GIS Cut Line= 3
      1666189.30      6907610.48      1666355.00      6907938.00
      1666854.97      6908737.96
#Sta/Elev= 30
  4632.0 1876.26  4819.7 1870.56  4829.1 1870.61  4923.9 1868.03  4940.5 1867.03
  4976.6 1865.84  4988.2 1864.90  4988.6 1864.40  4992.8 1864.40  4993.2 1864.90
  5034.4 1867.42  5079.8 1867.80  5143.5 1870.21  5426.5 1874.80  5499.6 1876.40
  5506.1 1876.84  5515.0 1876.67  5520.9 1877.36  5536.2 1877.08  5624.1 1879.02
  5651.8 1880.41  5667.1 1881.64  5688.3 1882.42  5703.7 1883.56  5709.5 1883.52
  5740.2 1885.51  5848.1 1888.89  5898.2 1890.82  5913.6 1892.15  5942.4 1893.15
#Mann=3,-1,0
  4632.0    0.05       0  4988.2    0.03       0  4993.2    0.05       0
Bank Sta=4988.2,4993.2
Exp/Cntr=0.3,0.1

Type RM Length L Ch R = 1,9150,475,475,475
BEGIN DESCRIPTION:
Deadman 35 13.0
END DESCRIPTION:
XS GIS Cut Line= 3
      1665654.99      6907637.99      1665905.00      6908038.00
      1666705.00      6908788.00
#Sta/Elev= 30
  4534.5 1885.57  4621.2 1880.30  4673.1 1875.22  4911.9 1866.96  4934.9 1865.38
  4940.8 1864.21  4947.2 1863.73  4977.3 1863.17  4990.1 1861.81  4990.5 1861.31
  4994.8 1861.31  4995.1 1861.81  4998.5 1862.57  5009.6 1862.76  5013.3 1863.59
  5027.5 1864.28  5112.4 1865.18  5126.6 1865.28  5161.8 1863.28  5176.0 1863.14
  5197.4 1864.44  5289.3 1865.93  5310.3 1867.43  5381.1 1869.27  5529.6 1871.43
  5628.8 1874.51  5763.1 1877.69  5819.7 1880.22  6018.0 1886.49  6102.8 1890.78
#Mann=3,-1,0
  4534.5    0.05       0  4990.1    0.03       0  4995.1    0.05       0
Bank Sta=4990.1,4995.1
Exp/Cntr=0.3,0.1

Type RM Length L Ch R = 1,8675,466,466,466
BEGIN DESCRIPTION:
Deadman 35 12.0
END DESCRIPTION:
XS GIS Cut Line= 3
      1665605.00      6907587.97      1665705.00      6908388.00
      1666055.02      6908788.02
#Sta/Elev= 30
  4193.3 1891.54  4213.5 1890.07  4253.8 1885.79  4344.5 1880.82  4364.7 1879.13
  4392.4 1875.97  4415.0 1874.45  4656.9 1866.54  4697.2 1864.93  4727.5 1863.13
  4777.8 1862.91  4795.5 1861.76  4818.2 1861.68  4888.7 1863.45  4961.8 1861.12
  4986.9 1859.25  4987.3 1858.75  4991.7 1858.75  4992.1 1859.25  4997.0 1860.30
  5002.9 1860.30  5006.7 1861.33  5020.9 1862.32  5049.4 1863.34  5092.1 1864.21
  5169.9 1867.14  5198.4 1867.75  5205.0 1868.38  5297.1 1870.98  5531.1 1876.76
#Mann=3,-1,0
  4193.3    0.05       0  4986.9    0.05       0  4992.1    0.05       0
Bank Sta=4986.9,4992.1
Exp/Cntr=0.3,0.1

Type RM Length L Ch R = 1,8209,447,447,447
BEGIN DESCRIPTION:
Deadman 35 11.0
END DESCRIPTION:
XS GIS Cut Line= 3
      1665154.99      6907937.97      1665255.00      6908338.00
      1665955.03      6909138.04
#Sta/Elev= 30
  4587.8 1877.03  4611.0 1875.73  4647.1 1872.00  4701.2 1868.56  4775.9 1866.08
  4858.4 1862.85  4876.4 1861.49  4899.6 1861.23  4928.0 1859.76  4935.7 1858.22
  4940.9 1858.65  4974.3 1853.75  4974.7 1853.25  4979.1 1853.25  4979.5 1853.75
  4982.1 1854.51  5003.5 1854.71  5007.3 1855.86  5028.1 1857.87  5056.6 1857.94
  5064.2 1859.03  5078.4 1859.51  5156.3 1858.80  5262.6 1862.81  5383.1 1865.46
  5553.0 1868.32  5822.5 1874.53  5878.5 1876.50  5921.3 1879.26  6063.2 1884.95
#Mann=3,-1,0
  4587.8    0.05       0  4974.3    0.05       0  4979.5    0.05       0
Bank Sta=4974.3,4979.5
Exp/Cntr=0.3,0.1

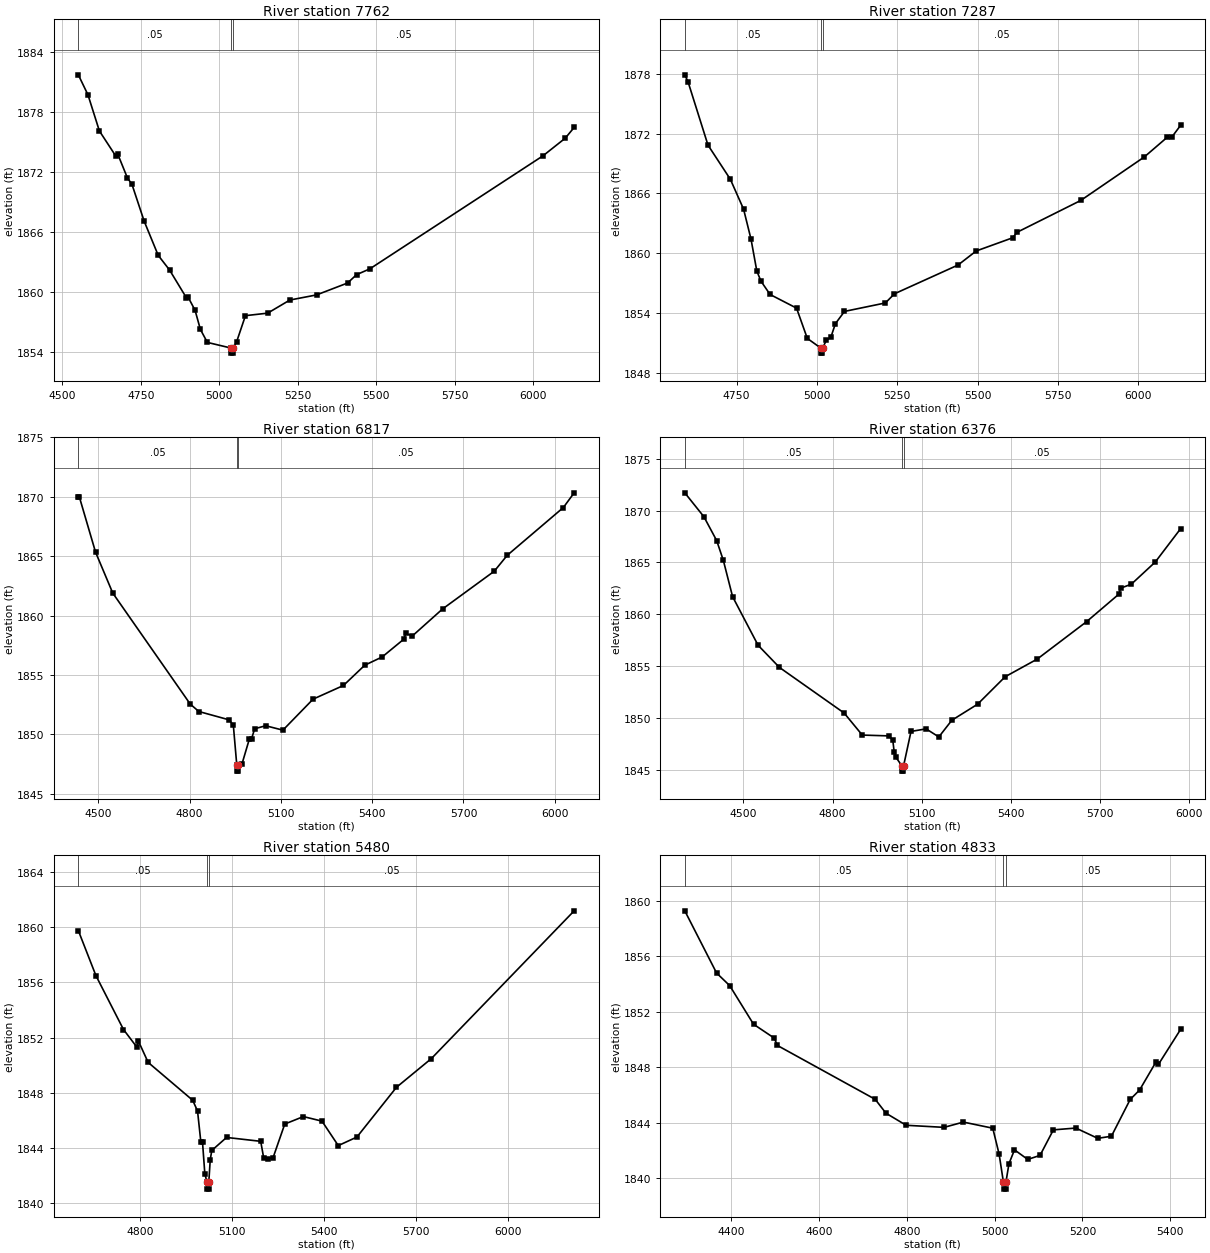
Type RM Length L Ch R = 1,7762,475,475,475
BEGIN DESCRIPTION:
Deadman 35 10.0
END DESCRIPTION:
XS GIS Cut Line= 3
      1664655.02      6907988.04      1664855.00      6908388.00
      1665654.97      6909187.97
#Sta/Elev= 30
  4551.4 1881.71  4582.1 1879.71  4618.4 1876.11  4671.5 1873.56  4677.1 1873.78
  4707.9 1871.40  4721.9 1870.80  4761.0 1867.10  4805.7 1863.69  4842.0 1862.22
  4895.1 1859.47  4900.7 1859.53  4923.1 1858.20  4939.9 1856.30  4962.2 1855.00
  5038.3 1854.43  5038.7 1853.93  5043.2 1853.93  5043.6 1854.43  5055.1 1855.04
  5083.4 1857.67  5154.1 1857.92  5224.8 1859.23  5309.7 1859.74  5408.7 1860.93
  5437.0 1861.76  5479.4 1862.34  6030.9 1873.63  6101.7 1875.39  6129.9 1876.46
#Mann=3,-1,0
  4551.4    0.05       0  5038.3    0.03       0  5043.6    0.05       0
Bank Sta=5038.3,5043.6
Exp/Cntr=0.3,0.1

Type RM Length L Ch R = 1,7287,470,470,470
BEGIN DESCRIPTION:
Deadman 35 9.0
END DESCRIPTION:
XS GIS Cut Line= 3
      1664354.99      6908187.95      1664455.00      6908588.00
      1665254.98      6909387.98
#Sta/Elev= 30
  4588.5 1877.90  4598.9 1877.17  4660.7 1870.84  4730.3 1867.41  4771.5 1864.41
  4794.7 1861.39  4812.7 1858.20  4825.6 1857.18  4854.0 1855.84  4936.4 1854.47
  4969.9 1851.43  5012.3 1850.45  5012.7 1849.95  5017.2 1849.95  5017.6 1850.45
  5029.1 1851.25  5043.3 1851.55  5057.4 1852.91  5085.7 1854.14  5213.0 1854.99
  5241.3 1855.91  5439.3 1858.80  5495.8 1860.21  5609.0 1861.53  5623.1 1862.09
  5821.1 1865.28  6019.1 1869.65  6089.8 1871.61  6103.9 1871.61  6132.2 1872.83
#Mann=3,-1,0
  4588.5    0.05       0  5012.3    0.03       0  5017.6    0.05       0
Bank Sta=5012.3,5017.6
Exp/Cntr=0.3,0.1

Type RM Length L Ch R = 1,6817,441,441,441
BEGIN DESCRIPTION:
Deadman 35 8.0
END DESCRIPTION:
XS GIS Cut Line= 3
      1663705.02      6908438.02      1664105.00      6908838.00
      1664805.02      6909638.02
#Sta/Elev= 30
  4434.8 1869.97  4438.3 1869.97  4491.3 1865.34  4547.9 1861.89  4802.5 1852.54
  4830.7 1851.92  4929.7 1851.22  4943.9 1850.78  4955.3 1847.40  4955.7 1846.90
  4960.3 1846.90  4960.7 1847.40  4972.2 1847.49  4996.9 1849.63  5003.8 1849.63
  5014.2 1850.47  5050.3 1850.72  5106.8 1850.35  5205.9 1852.96  5305.6 1854.11
  5375.8 1855.82  5432.8 1856.51  5504.0 1858.01  5510.6 1858.49  5532.0 1858.28
  5631.1 1860.55  5801.0 1863.73  5843.7 1865.07  6027.9 1869.09  6063.5 1870.33
#Mann=3,-1,0
  4434.8    0.05       0  4955.3    0.05       0  4960.7    0.05       0
Bank Sta=4955.3,4960.7
Exp/Cntr=0.3,0.1

Type RM Length L Ch R = 1,6376,896,896,896
BEGIN DESCRIPTION:
Deadman 35 7.0
END DESCRIPTION:
XS GIS Cut Line= 3
      1663554.99      6908487.99      1663805.00      6909138.00
      1664605.03      6909688.02
#Sta/Elev= 30
  4303.2 1871.72  4367.5 1869.41  4410.4 1867.11  4432.9 1865.19  4463.9 1861.70
  4549.6 1857.01  4621.4 1854.87  4838.9 1850.47  4900.0 1848.34  4990.0 1848.26
  5002.7 1847.83  5007.1 1846.75  5013.1 1846.20  5033.3 1845.36  5033.7 1844.86
  5038.3 1844.86  5038.8 1845.36  5063.9 1848.69  5114.6 1848.94  5157.4 1848.16
  5201.2 1849.77  5287.8 1851.32  5380.5 1853.97  5488.1 1855.67  5654.9 1859.30
  5762.8 1861.94  5768.8 1862.52  5804.7 1862.90  5885.2 1865.04  5970.5 1868.26
#Mann=3,-1,0
  4303.2    0.05       0  5033.3    0.05       0  5038.8    0.05       0
Bank Sta=5033.3,5038.8
Exp/Cntr=0.3,0.1

Type RM Length L Ch R = 1,5480,647,647,647
BEGIN DESCRIPTION:
Deadman 35 6.0
END DESCRIPTION:
XS GIS Cut Line= 3
      1662955.02      6909038.04      1663155.00      6909388.00
      1664354.98      6909588.00
#Sta/Elev= 30
  4597.3 1859.74  4654.8 1856.48  4744.8 1852.58  4788.0 1851.32  4793.8 1851.73
  4825.4 1850.20  4970.9 1847.46  4986.7 1846.68  4997.5 1844.44  5002.9 1844.44
  5010.5 1842.14  5017.8 1841.53  5018.3 1841.03  5023.0 1841.03  5023.4 1841.53
  5028.2 1843.17  5033.3 1843.83  5081.5 1844.77  5193.0 1844.49  5203.1 1843.25
  5215.8 1843.22  5233.5 1843.31  5271.6 1845.74  5332.4 1846.28  5393.2 1845.95
  5446.4 1844.18  5507.3 1844.80  5636.5 1848.40  5750.6 1850.48  6216.9 1861.17
#Mann=3,-1,0
  4597.3    0.05       0  5017.8    0.05       0  5023.4    0.05       0
Bank Sta=5017.8,5023.4
Exp/Cntr=0.3,0.1

Type RM Length L Ch R = 1,4833,250,250,250
BEGIN DESCRIPTION:
Mapping XS bae82c33
END DESCRIPTION:
XS GIS Cut Line= 3
      1662902.68      6909078.12      1663087.90      6909553.03
      1663619.84      6909871.24
#Sta/Elev= 30
  4294.0 1859.26  4366.4 1854.78  4396.3 1853.87  4450.6 1851.09  4497.8 1850.09
  4505.0 1849.56  4727.8 1845.68  4752.3 1844.68  4798.3 1843.81  4884.7 1843.66
  4928.6 1844.04  4995.6 1843.60  5010.1 1841.73  5019.9 1839.71  5020.4 1839.21
  5025.2 1839.21  5025.6 1839.71  5032.5 1841.04  5045.1 1842.04  5075.3 1841.35
  5103.3 1841.64  5133.7 1843.48  5184.9 1843.61  5234.8 1842.87  5265.9 1843.02
  5308.7 1845.67  5330.1 1846.35  5367.1 1848.35  5372.9 1848.19  5423.6 1850.72
#Mann=3,-1,0
  4294.0    0.05       0  5019.9    0.05       0  5025.6    0.05       0
Bank Sta=5019.9,5025.6
Exp/Cntr=0.3,0.1

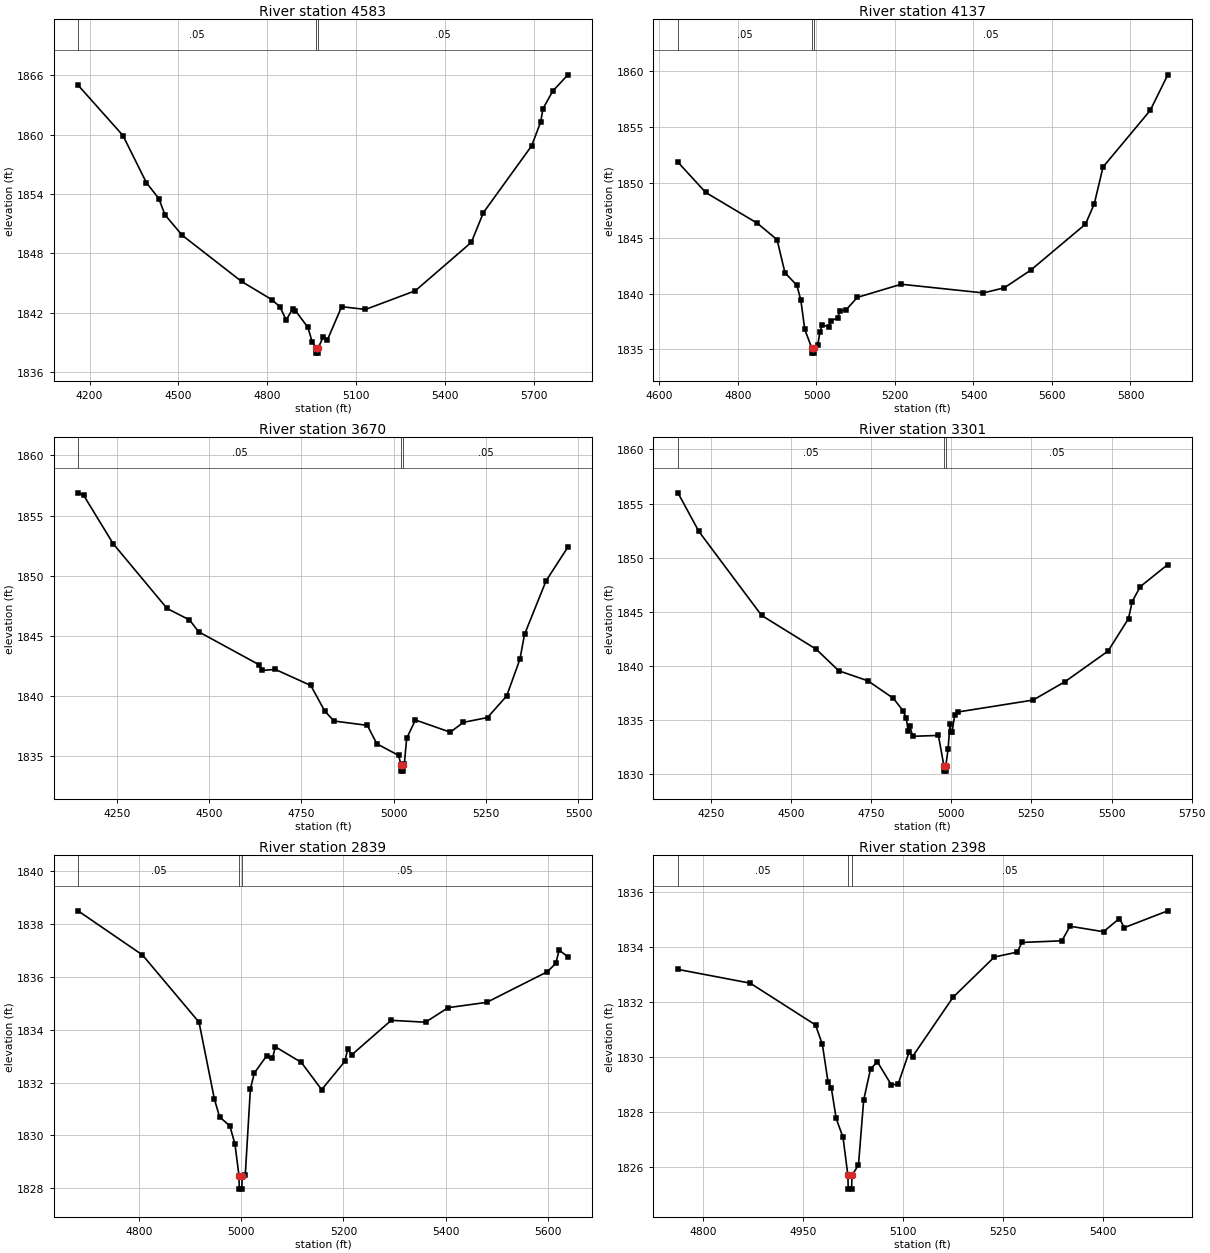
Type RM Length L Ch R = 1,4583,446,446,446
BEGIN DESCRIPTION:
Deadman 35 5.0
END DESCRIPTION:
XS GIS Cut Line= 3
      1662805.01      6908938.03      1663055.00      6909738.00
      1663205.01      6910538.04
#Sta/Elev= 30
  4161.3 1865.02  4312.7 1859.92  4391.8 1855.15  4433.7 1853.54  4454.6 1851.89
  4512.8 1849.82  4712.9 1845.15  4815.5 1843.30  4842.3 1842.58  4863.2 1841.26
  4885.7 1842.39  4894.6 1842.20  4936.6 1840.50  4950.7 1839.06  4965.0 1838.40
  4965.5 1837.90  4970.4 1837.90  4970.9 1838.40  4988.9 1839.58  5002.0 1839.21
  5050.3 1842.60  5130.8 1842.32  5298.7 1844.21  5487.8 1849.11  5528.5 1852.12
  5691.3 1858.88  5721.8 1861.31  5729.4 1862.64  5762.5 1864.42  5813.4 1866.06
#Mann=3,-1,0
  4161.3    0.05       0  4965.0    0.05       0  4970.9    0.05       0
Bank Sta=4965,4970.9
Exp/Cntr=0.3,0.1

Type RM Length L Ch R = 1,4137,467,467,467
BEGIN DESCRIPTION:
Deadman 35 4.0
END DESCRIPTION:
XS GIS Cut Line= 3
      1662655.00      6909288.01      1662705.00      6909638.00
      1663105.01      6910438.03
#Sta/Elev= 30
  4647.0 1851.83  4717.7 1849.11  4849.0 1846.35  4899.5 1844.87  4919.7 1841.89
  4950.0 1840.77  4960.1 1839.44  4970.2 1836.80  4987.5 1835.17  4988.0 1834.67
  4992.9 1834.67  4993.4 1835.17  5003.3 1835.41  5008.9 1836.61  5014.5 1837.19
  5031.3 1837.06  5036.9 1837.59  5053.6 1837.82  5059.2 1838.43  5076.0 1838.58
  5104.0 1839.68  5215.8 1840.86  5425.4 1840.08  5478.5 1840.54  5545.6 1842.12
  5685.3 1846.26  5707.7 1848.08  5730.1 1851.40  5850.2 1856.48  5895.0 1859.68
#Mann=3,-1,0
  4647.0    0.05       0  4987.5    0.05       0  4993.4    0.05       0
Bank Sta=4987.5,4993.4
Exp/Cntr=0.3,0.1

Type RM Length L Ch R = 1,3670,369,369,369
BEGIN DESCRIPTION:
Deadman 35 3.0
END DESCRIPTION:
XS GIS Cut Line= 3
      1662205.01      6909238.04      1662505.00      6910038.00
      1662755.02      6910438.04
#Sta/Elev= 30
  4145.2 1856.89  4160.3 1856.69  4240.4 1852.65  4386.3 1847.26  4446.9 1846.31
  4471.8 1845.32  4636.4 1842.56  4642.7 1842.10  4679.2 1842.19  4775.3 1840.85
  4813.5 1838.70  4838.5 1837.89  4928.4 1837.53  4954.2 1835.99  5013.1 1835.03
  5019.6 1834.22  5020.1 1833.72  5025.0 1833.72  5025.5 1834.22  5028.5 1834.32
  5034.9 1836.45  5058.5 1837.98  5152.9 1836.96  5188.2 1837.78  5253.7 1838.18
  5305.6 1839.98  5341.5 1843.04  5353.9 1845.10  5412.3 1849.57  5471.3 1852.37
#Mann=3,-1,0
  4145.2    0.05       0  5019.6    0.05       0  5025.5    0.05       0
Bank Sta=5019.6,5025.5
Exp/Cntr=0.3,0.1

Type RM Length L Ch R = 1,3301,462,462,462
BEGIN DESCRIPTION:
Deadman 35 2.0
END DESCRIPTION:
XS GIS Cut Line= 3
      1662105.00      6909287.95      1662170.22      6910137.75
      1662399.10      6910773.30
#Sta/Elev= 30
  4147.7 1855.99  4213.0 1852.42  4408.5 1844.66  4579.0 1841.53  4649.2 1839.54
  4740.1 1838.61  4819.7 1836.99  4849.8 1835.84  4859.8 1835.17  4865.7 1833.99
  4870.7 1834.47  4879.9 1833.48  4960.1 1833.56  4977.2 1830.76  4977.7 1830.26
  4982.7 1830.26  4983.2 1830.76  4990.2 1832.27  4996.2 1834.62  4998.6 1833.91
  5002.8 1833.91  5010.9 1835.41  5021.5 1835.73  5255.4 1836.83  5354.9 1838.53
  5489.2 1841.36  5553.0 1844.36  5564.5 1845.94  5589.9 1847.32  5675.5 1849.36
#Mann=3,-1,0
  4147.7    0.05       0  4977.2    0.05       0  4983.2    0.05       0
Bank Sta=4977.2,4983.2
Exp/Cntr=0.3,0.1

Type RM Length L Ch R = 1,2839,441,441,441
BEGIN DESCRIPTION:
Mapping XS 83f14bcc
END DESCRIPTION:
XS GIS Cut Line= 3
      1661738.26      6909802.54      1661773.42      6910148.31
      1662037.14      6910699.19
#Sta/Elev= 30
  4680.8 1838.49  4806.9 1836.82  4917.5 1834.28  4947.6 1831.37  4957.7 1830.70
  4977.8 1830.36  4987.8 1829.67  4995.7 1828.47  4996.2 1827.97  5001.3 1827.97
  5001.8 1828.47  5007.9 1828.49  5018.0 1831.76  5025.7 1832.36  5050.2 1833.02
  5061.2 1832.92  5066.8 1833.35  5117.7 1832.76  5157.4 1831.73  5202.8 1832.80
  5208.3 1833.25  5216.5 1833.05  5293.4 1834.35  5360.6 1834.28  5405.0 1834.83
  5480.3 1835.03  5599.2 1836.19  5615.6 1836.51  5621.9 1837.01  5639.1 1836.75
#Mann=3,-1,0
  4680.8    0.05       0  4995.7    0.03       0  5001.8    0.05       0
Bank Sta=4995.7,5001.8
Exp/Cntr=0.3,0.1

Type RM Length L Ch R = 1,2398,390,390,390
BEGIN DESCRIPTION:
Mapping XS 2abc244e
END DESCRIPTION:
XS GIS Cut Line= 3
      1661374.98      6910335.85      1661896.49      6910470.62
      1661960.48      6910656.79
#Sta/Elev= 30
  4762.4 1833.17  4870.9 1832.67  4969.0 1831.15  4979.3 1830.44  4987.7 1829.09
  4992.8 1828.85  5000.0 1827.75  5010.3 1827.06  5017.6 1825.68  5018.1 1825.18
  5023.2 1825.18  5023.7 1825.68  5033.5 1826.06  5041.3 1828.42  5051.6 1829.55
  5061.9 1829.81  5082.6 1828.98  5092.9 1828.99  5109.6 1830.17  5114.7 1830.00
  5175.6 1832.16  5237.5 1833.62  5272.1 1833.80  5278.8 1834.15  5338.9 1834.21
  5351.1 1834.74  5401.4 1834.54  5425.2 1835.02  5432.7 1834.69  5497.9 1835.30
#Mann=3,-1,0
  4762.4    0.05       0  5017.6    0.03       0  5023.7    0.05       0
Bank Sta=5017.6,5023.7
Exp/Cntr=0.3,0.1

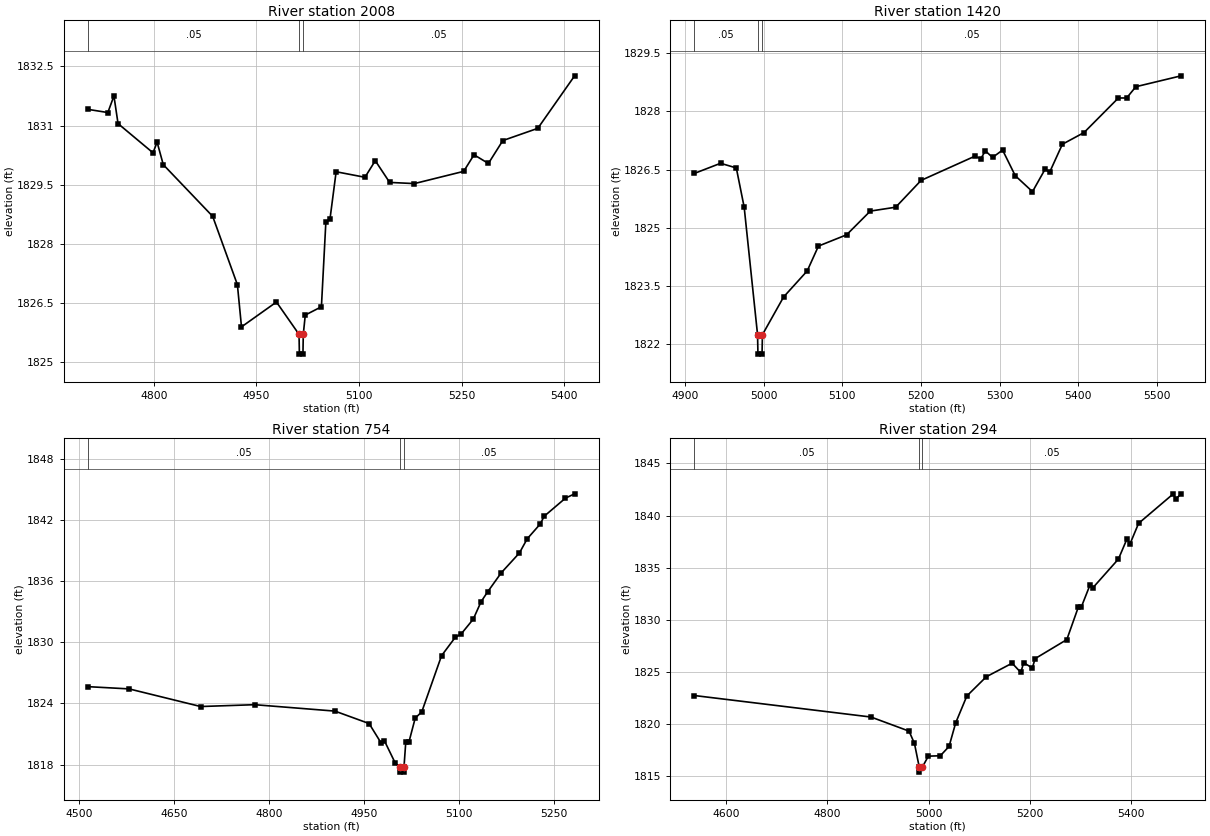
Type RM Length L Ch R = 1,2008,588,588,588
BEGIN DESCRIPTION:
Mapping XS 7e056ec0
END DESCRIPTION:
XS GIS Cut Line= 2
      1661230.88      6910550.44      1661823.28      6910943.79
#Sta/Elev= 30
  4703.9 1831.41  4732.9 1831.33  4741.8 1831.75  4747.8 1831.05  4798.9 1830.31
  4804.9 1830.58  4813.9 1830.01  4886.1 1828.70  4922.2 1826.97  4928.2 1825.90
  4979.3 1826.53  5012.3 1825.71  5012.8 1825.21  5018.0 1825.21  5018.5 1825.71
  5021.4 1826.20  5045.0 1826.41  5051.5 1828.56  5057.5 1828.63  5066.5 1829.83
  5108.6 1829.69  5123.7 1830.11  5144.7 1829.56  5180.8 1829.53  5252.9 1829.84
  5268.0 1830.26  5289.0 1830.04  5310.1 1830.62  5361.2 1830.93  5415.0 1832.26
#Mann=3,-1,0
  4703.9    0.05       0  5012.3    0.05       0  5018.5    0.05       0
Bank Sta=5012.3,5018.5
Exp/Cntr=0.3,0.1

Type RM Length L Ch R = 1,1420,666,666,666
BEGIN DESCRIPTION:
Mapping XS 9e2c7336
END DESCRIPTION:
XS GIS Cut Line= 3
      1661021.88      6911091.86      1661273.60      6911077.61
      1661595.51      6910902.45
#Sta/Elev= 30
  4912.2 1826.40  4945.4 1826.66  4965.4 1826.54  4975.4 1825.53  4992.4 1822.25
  4992.9 1821.75  4998.1 1821.75  4998.6 1822.25  5025.5 1823.22  5055.5 1823.89
  5069.8 1824.53  5105.6 1824.82  5135.7 1825.43  5168.0 1825.53  5200.3 1826.22
  5268.4 1826.84  5276.3 1826.78  5282.0 1826.98  5291.1 1826.81  5303.9 1827.00
  5320.0 1826.34  5341.9 1825.93  5358.0 1826.51  5363.7 1826.43  5379.9 1827.15
  5407.4 1827.45  5451.1 1828.34  5461.6 1828.34  5473.3 1828.63  5530.8 1828.91
#Mann=3,-1,0
  4912.2    0.05       0  4992.4    0.03       0  4998.6    0.05       0
Bank Sta=4992.4,4998.6
Exp/Cntr=0.3,0.1

Type RM Length L Ch R = 1,754,460,460,460
BEGIN DESCRIPTION:
Mapping XS 05ac8279
END DESCRIPTION:
XS GIS Cut Line= 3
      1661112.14      6911329.36      1661378.08      6911562.06
      1661777.04      6911676.05
#Sta/Elev= 30
  4514.1 1825.65  4579.0 1825.43  4692.0 1823.70  4777.4 1823.88  4904.0 1823.25
  4957.9 1822.03  4976.8 1820.13  4982.0 1820.35  4999.5 1818.11  5006.7 1817.76
  5007.2 1817.26  5012.5 1817.26  5013.0 1817.76  5015.8 1820.19  5021.0 1820.26
  5030.7 1822.56  5041.1 1823.18  5072.3 1828.69  5093.8 1830.48  5103.5 1830.84
  5122.4 1832.28  5134.7 1833.99  5145.1 1834.96  5166.6 1836.83  5195.2 1838.77
  5207.5 1840.16  5228.3 1841.63  5234.2 1842.37  5268.0 1844.16  5282.4 1844.58
#Mann=3,-1,0
  4514.1    0.05       0  5006.7    0.05       0  5013.0    0.05       0
Bank Sta=5006.7,5013
Exp/Cntr=0.3,0.1

Type RM Length L Ch R = 1,294,0,0,0
BEGIN DESCRIPTION:
Deadman 35 1.0
END DESCRIPTION:
XS GIS Cut Line= 3
      1661029.99      6911462.98      1661196.83      6911894.13
      1661646.73      6912108.59
#Sta/Elev= 30
  4537.7 1822.75  4886.2 1820.69  4961.3 1819.34  4972.0 1818.16  4981.4 1815.91
  4981.9 1815.41  4987.8 1815.91  4999.4 1816.94  5023.1 1816.98  5040.3 1817.87
  5053.4 1820.13  5075.5 1822.71  5113.9 1824.55  5164.9 1825.85  5182.0 1824.96
  5187.6 1825.90  5204.7 1825.39  5210.3 1826.29  5272.8 1828.11  5295.5 1831.22
  5301.1 1831.19  5318.2 1833.30  5323.8 1833.05  5374.7 1835.83  5391.8 1837.78
  5397.4 1837.26  5414.5 1839.25  5482.6 1842.06  5488.2 1841.59  5498.4 1842.08
#Mann=3,-1,0
  4537.7    0.05       0  4981.4    0.05       0  4987.8    0.05       0
Bank Sta=4981.4,4987.8
Exp/Cntr=0.3,0.1

Chan Stop Cuts=-1