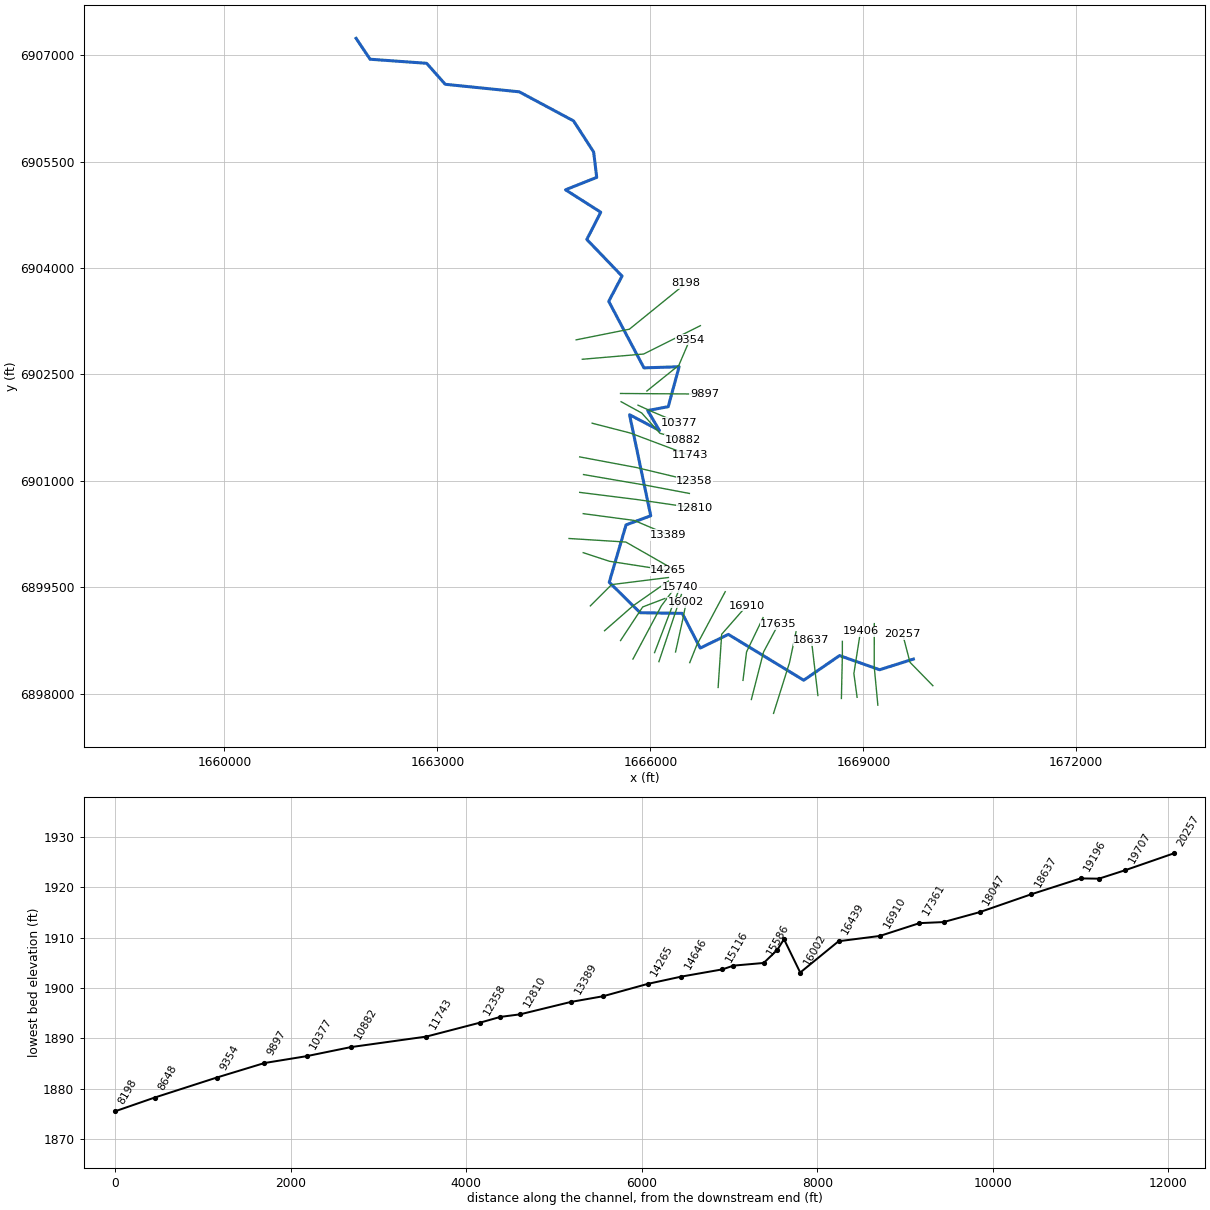
--- Deadman 36.prj (project) ---

Proj Title=Deadman 36 Base Level Engineering
Current Plan=p01
Default Exp/Contr=0.3,0.1
English Units
Geom File=g01
Flow File=f01
Plan File=p01
BEGIN DESCRIPTION:
Deadman 36
END DESCRIPTION:

--- Deadman 36.p01 (plan) ---

Plan Title=Multiple Run
Short Identifier=Multiple
Geom File=g01
Flow File=f01
Subcritical Flow
K Sum by GR= 0
Std Step Tol= 0.01
Critical Tol= 0.01
Num of Std Step Trials= 20
Max Error Tol= 0.3
Flow Tol Ratio= 0.001
Split Flow NTrial= 30
Split Flow Tol= 0.02
Split Flow Ratio= 0.02
Log Output Level= 0
Friction Slope Method= 1
Unsteady Friction Slope Method= 2
Unsteady Bridges Friction Slope Method= 1
Parabolic Critical Depth
Global Vel Dist=  1 , 1 , 1
Global Log Level= 0
CheckData=True
Encroach Param= -1, 0, 0, 0
BEGIN DESCRIPTION:
Multiple Run
END DESCRIPTION:

--- Deadman 36.f01 (steady flow) ---

Flow Title=Multiple
Number of Profiles=7
Profile Names=10-year,25-year,50-year,1pct_min,100-year,1pct_plu,500-year
River Rch & RM= Deadman 36,Reach-1,20257
     292     403     494     301     601    1199     902
River Rch & RM= Deadman 36,Reach-1,9354
     394     552     684     421     840    1677    1285
River Rch & RM= Deadman 36,Reach-1,7313
     460     649     808     500     997    1989    1538
Boundary for River Rch & Prof#=Deadman 36,Reach-1,1
Up Type=0
Dn Type=3
Dn Slope=0.01
Boundary for River Rch & Prof#=Deadman 36,Reach-1,2
Up Type=0
Dn Type=3
Dn Slope=0.01
Boundary for River Rch & Prof#=Deadman 36,Reach-1,3
Up Type=0
Dn Type=3
Dn Slope=0.01
Boundary for River Rch & Prof#=Deadman 36,Reach-1,4
Up Type=0
Dn Type=3
Dn Slope=0.01
Boundary for River Rch & Prof#=Deadman 36,Reach-1,5
Up Type=0
Dn Type=3
Dn Slope=0.01
Boundary for River Rch & Prof#=Deadman 36,Reach-1,6
Up Type=0
Dn Type=3
Dn Slope=0.01
Boundary for River Rch & Prof#=Deadman 36,Reach-1,7
Up Type=0
Dn Type=3
Dn Slope=0.01

--- Deadman 36.g01 (geometry) ---

Geom Title=Existing Conditions

River Reach=Deadman 36,Reach-1
Reach XY= 30
      1669705.00      6898488.00      1669229.90      6898337.78
      1668665.62      6898537.40      1668160.83      6898190.06
      1667099.14      6898835.95      1666702.57      6898643.40
      1666449.74      6899132.53      1665856.50      6899141.46
      1665421.28      6899571.26      1665658.07      6900379.70
      1666005.49      6900508.12      1665707.06      6901932.56
      1666128.59      6901710.84      1665962.41      6901991.45
      1666252.09      6902045.91      1666405.62      6902608.61
      1665910.00      6902593.00      1665413.99      6903530.99
      1665601.46      6903886.53      1665105.33      6904403.00
      1665301.67      6904786.68      1664805.24      6905103.22
      1665244.66      6905277.76      1665201.24      6905636.44
      1664918.22      6906074.38      1664153.42      6906484.17
      1663110.97      6906590.14      1662849.16      6906885.95
      1662052.34      6906943.45      1661855.00      6907238.00

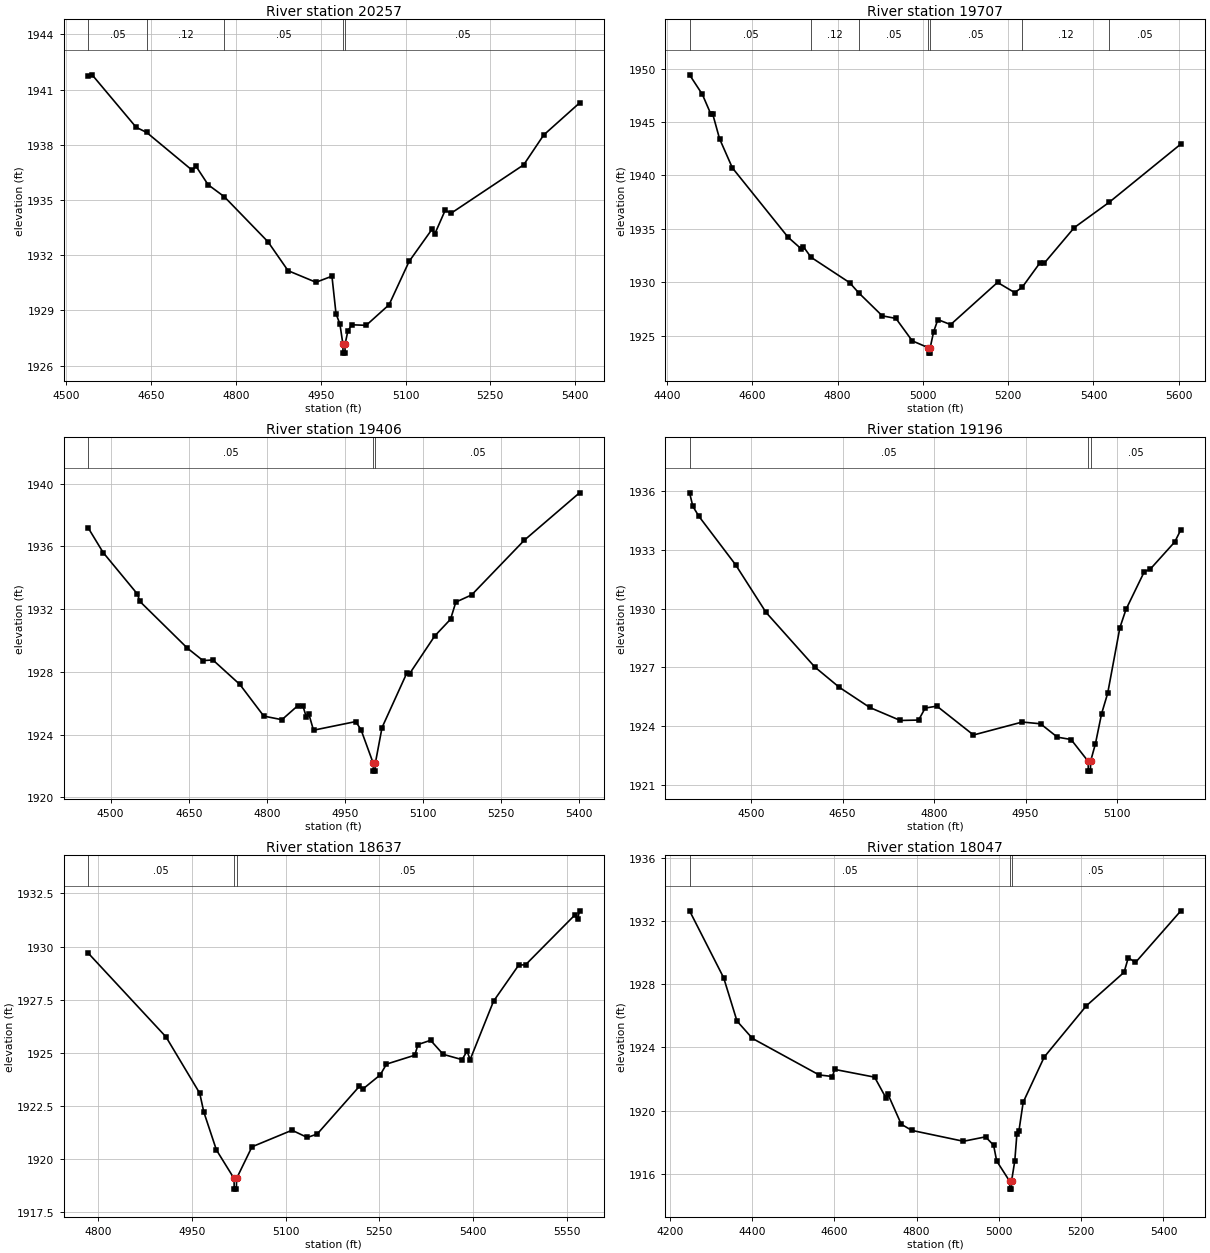
Type RM Length L Ch R = 1,20257,550,550,550
BEGIN DESCRIPTION:
Deadman 36 34.0
END DESCRIPTION:
XS GIS Cut Line= 3
      1669979.97      6898113.03      1669657.55      6898443.22
      1669554.99      6898838.02
#Sta/Elev= 30
  4538.5 1941.75  4545.4 1941.80  4623.3 1938.95  4641.9 1938.67  4722.3 1936.62
  4729.3 1936.83  4750.6 1935.83  4779.2 1935.18  4856.6 1932.73  4892.1 1931.16
  4941.5 1930.53  4969.8 1930.86  4977.0 1928.82  4983.9 1928.26  4989.1 1927.18
  4989.4 1926.68  4992.9 1926.68  4993.1 1927.18  4998.1 1927.90  5005.1 1928.22
  5030.4 1928.19  5070.9 1929.31  5106.3 1931.66  5146.9 1933.41  5152.0 1933.17
  5170.2 1934.44  5180.6 1934.28  5309.1 1936.91  5344.5 1938.53  5407.9 1940.27
#Mann=5,-1,0
  4538.5    0.05       0  4641.9    0.12       0  4779.2    0.05       0
  4989.1    0.03       0  4993.1    0.05       0
Bank Sta=4989.1,4993.1
Exp/Cntr=0.3,0.1

Type RM Length L Ch R = 1,19707,301,301,301
BEGIN DESCRIPTION:
Deadman 36 33.0
END DESCRIPTION:
XS GIS Cut Line= 3
      1669205.00      6897838.02      1669153.73      6898383.51
      1669155.00      6898988.02
#Sta/Elev= 30
  4452.6 1949.41  4482.7 1947.57  4501.9 1945.79  4506.9 1945.74  4522.9 1943.43
  4553.0 1940.70  4683.6 1934.21  4713.7 1933.15  4719.2 1933.34  4737.6 1932.33
  4827.9 1929.96  4849.2 1929.01  4904.6 1926.85  4936.6 1926.61  4974.9 1924.51
  5013.0 1923.86  5013.2 1923.36  5016.7 1923.36  5017.0 1923.86  5025.0 1925.35
  5035.0 1926.50  5065.0 1926.03  5175.0 1929.98  5215.0 1929.03  5232.6 1929.51
  5275.0 1931.84  5285.0 1931.80  5355.0 1935.11  5436.9 1937.48  5605.0 1942.93
#Mann=7,-1,0
  4452.6    0.05       0  4737.6    0.12       0  4849.2    0.05       0
  5013.0    0.03       0  5017.0    0.05       0  5232.6    0.12       0
  5436.9    0.05       0
Bank Sta=5013,5017
Exp/Cntr=0.3,0.1

Type RM Length L Ch R = 1,19406,210,210,210
BEGIN DESCRIPTION:
Mapping XS 038ae4d7
END DESCRIPTION:
XS GIS Cut Line= 3
      1668912.67      6897949.56      1668867.29      6898284.25
      1668960.87      6898882.62
#Sta/Elev= 30
  4457.0 1937.18  4485.7 1935.61  4551.3 1932.97  4556.3 1932.49  4647.2 1929.52
  4677.4 1928.72  4696.4 1928.76  4748.1 1927.20  4794.1 1925.18  4828.9 1924.95
  4859.3 1925.84  4869.4 1925.81  4875.7 1925.13  4880.8 1925.29  4889.6 1924.28
  4970.6 1924.83  4980.7 1924.32  5004.3 1922.17  5004.5 1921.67  5008.0 1921.67
  5008.3 1922.17  5021.2 1924.45  5069.0 1927.94  5074.0 1927.88  5122.4 1930.29
  5152.8 1931.36  5162.9 1932.45  5193.3 1932.91  5294.5 1936.40  5400.4 1939.42
#Mann=3,-1,0
  4457.0    0.05       0  5004.3    0.05       0  5008.3    0.05       0
Bank Sta=5004.3,5008.3
Exp/Cntr=0.3,0.1

Type RM Length L Ch R = 1,19196,559,559,559
BEGIN DESCRIPTION:
Deadman 36 32.0
END DESCRIPTION:
XS GIS Cut Line= 3
      1668691.45      6897932.61      1668705.00      6898538.00
      1668705.00      6898737.96
#Sta/Elev= 30
  4399.2 1935.89  4404.6 1935.20  4414.6 1934.69  4474.6 1932.23  4524.6 1929.80
  4604.6 1927.02  4644.6 1925.99  4694.7 1924.96  4744.7 1924.30  4774.7 1924.32
  4785.5 1924.93  4804.7 1925.03  4864.7 1923.56  4944.7 1924.22  4974.7 1924.13
  5002.2 1923.45  5024.7 1923.33  5052.7 1922.22  5053.0 1921.72  5056.5 1921.72
  5056.7 1922.22  5064.7 1923.12  5074.7 1924.64  5084.7 1925.68  5104.7 1929.02
  5114.7 1929.95  5144.7 1931.87  5154.7 1932.01  5194.7 1933.39  5204.7 1934.01
#Mann=3,-1,0
  4399.2    0.05       0  5052.7    0.05       0  5056.7    0.05       0
Bank Sta=5052.7,5056.7
Exp/Cntr=0.3,0.1

Type RM Length L Ch R = 1,18637,590,590,590
BEGIN DESCRIPTION:
Mapping XS 15ee7aba
END DESCRIPTION:
XS GIS Cut Line= 2
      1668360.49      6897974.52      1668269.50      6898754.43
#Sta/Elev= 30
  4784.7 1929.69  4909.0 1925.75  4962.9 1923.10  4969.4 1922.22  4989.6 1920.43
  5017.8 1919.09  5018.0 1918.59  5021.5 1918.59  5021.8 1919.09  5046.4 1920.58
  5110.4 1921.36  5134.8 1921.02  5150.6 1921.18  5218.2 1923.43  5223.3 1923.29
  5251.3 1923.96  5261.4 1924.47  5306.7 1924.89  5311.7 1925.39  5331.9 1925.59
  5352.0 1924.93  5382.2 1924.68  5390.1 1925.08  5395.1 1924.68  5432.5 1927.43
  5472.8 1929.13  5483.6 1929.14  5562.0 1931.47  5567.0 1931.30  5569.9 1931.68
#Mann=3,-1,0
  4784.7    0.05       0  5017.8    0.03       0  5021.8    0.05       0
Bank Sta=5017.8,5021.8
Exp/Cntr=0.3,0.1

Type RM Length L Ch R = 1,18047,412,412,412
BEGIN DESCRIPTION:
Deadman 36 31.0
END DESCRIPTION:
XS GIS Cut Line= 3
      1667735.49      6897722.86      1667960.98      6898440.36
      1668052.32      6898873.02
#Sta/Elev= 30
  4247.9 1932.65  4330.8 1928.41  4363.2 1925.67  4400.8 1924.57  4562.8 1922.26
  4595.2 1922.16  4600.5 1922.61  4697.7 1922.12  4724.8 1920.83  4730.1 1921.04
  4762.5 1919.14  4787.9 1918.75  4913.7 1918.06  4967.4 1918.34  4987.0 1917.81
  4994.5 1916.81  5026.0 1915.53  5026.3 1915.03  5030.2 1915.03  5030.6 1915.53
  5038.5 1916.82  5043.6 1918.52  5048.7 1918.74  5058.9 1920.53  5110.0 1923.39
  5212.2 1926.63  5304.2 1928.76  5314.4 1929.68  5331.9 1929.38  5442.2 1932.65
#Mann=3,-1,0
  4247.9    0.05       0  5026.0    0.03       0  5030.6    0.05       0
Bank Sta=5026,5030.6
Exp/Cntr=0.3,0.1

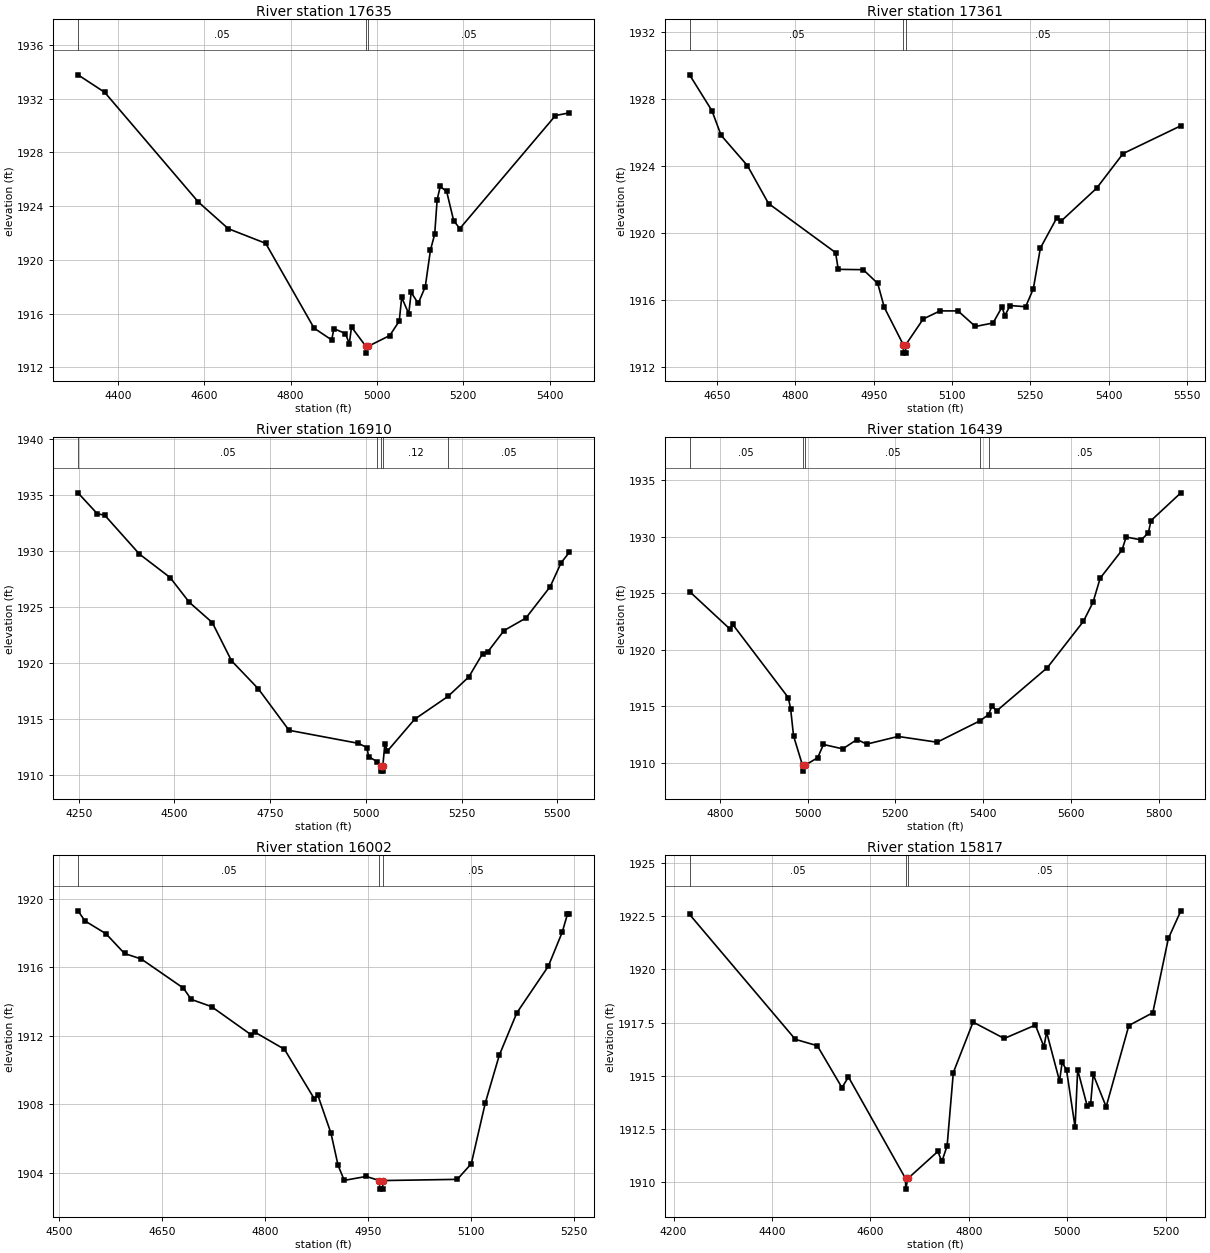
Type RM Length L Ch R = 1,17635,274,274,274
BEGIN DESCRIPTION:
Deadman 36 30.0
END DESCRIPTION:
XS GIS Cut Line= 3
      1667422.99      6897918.17      1667594.95      6898588.78
      1667804.90      6898981.47
#Sta/Elev= 30
  4307.7 1933.77  4369.5 1932.47  4586.3 1924.31  4655.7 1922.32  4742.4 1921.23
  4854.4 1914.92  4895.2 1914.04  4900.3 1914.88  4926.9 1914.52  4936.0 1913.77
  4941.1 1915.00  4974.4 1913.56  4974.7 1913.06  4979.1 1913.56  5029.7 1914.37
  5051.6 1915.44  5057.3 1917.21  5073.6 1915.99  5079.3 1917.58  5095.5 1916.76
  5111.8 1917.99  5123.9 1920.73  5133.7 1921.91  5139.4 1924.48  5146.5 1925.46
  5161.4 1925.09  5177.6 1922.92  5191.9 1922.33  5413.4 1930.74  5445.3 1930.94
#Mann=3,-1,0
  4307.7    0.05       0  4974.4    0.05       0  4979.1    0.05       0
Bank Sta=4974.4,4979.1
Exp/Cntr=0.3,0.1

Type RM Length L Ch R = 1,17361,451,451,451
BEGIN DESCRIPTION:
Deadman 36 29.0
END DESCRIPTION:
XS GIS Cut Line= 3
      1667305.00      6898188.02      1667355.00      6898588.00
      1667587.90      6899072.65
#Sta/Elev= 30
  4597.4 1929.46  4640.2 1927.32  4657.8 1925.85  4708.2 1924.04  4748.6 1921.78
  4877.0 1918.85  4882.1 1917.85  4930.0 1917.83  4957.7 1917.01  4970.3 1915.58
  5006.7 1913.35  5007.0 1912.85  5011.0 1912.85  5011.4 1913.35  5044.9 1914.89
  5077.0 1915.37  5111.4 1915.37  5144.7 1914.44  5178.6 1914.65  5195.7 1915.60
  5201.2 1915.09  5211.3 1915.69  5241.0 1915.62  5255.7 1916.69  5269.2 1919.12
  5300.1 1920.89  5308.9 1920.73  5376.8 1922.69  5427.6 1924.76  5538.2 1926.42
#Mann=3,-1,0
  4597.4    0.05       0  5006.7    0.05       0  5011.4    0.05       0
Bank Sta=5006.7,5011.4
Exp/Cntr=0.3,0.1

Type RM Length L Ch R = 1,16910,471,471,471
BEGIN DESCRIPTION:
Deadman 36 28.0
END DESCRIPTION:
XS GIS Cut Line= 3
      1666955.00      6898088.02      1667005.00      6898838.00
      1667354.97      6899237.96
#Sta/Elev= 30
  4248.3 1935.19  4298.4 1933.33  4318.4 1933.18  4408.6 1929.72  4488.8 1927.62
  4538.9 1925.41  4599.1 1923.59  4649.2 1920.18  4719.3 1917.67  4799.5 1913.96
  4979.9 1912.80  5003.3 1912.42  5007.1 1911.61  5029.9 1911.15  5039.8 1910.81
  5040.1 1910.31  5044.2 1910.31  5044.6 1910.81  5049.8 1912.77  5056.4 1912.10
  5127.6 1914.95  5214.6 1916.99  5269.0 1918.73  5305.1 1920.81  5318.8 1920.98
  5361.1 1922.88  5418.0 1923.99  5481.6 1926.80  5510.1 1928.94  5531.4 1929.86
#Mann=5,-1,0
  4248.3    0.05       0  5029.9    0.12       0  5039.8    0.03       0
  5044.6    0.12       0  5214.6    0.05       0
Bank Sta=5039.8,5044.6
Exp/Cntr=0.3,0.1

Type RM Length L Ch R = 1,16439,437,437,437
BEGIN DESCRIPTION:
Deadman 36 27.0
END DESCRIPTION:
XS GIS Cut Line= 3
      1666555.01      6898438.02      1666655.00      6898688.00
      1667054.98      6899437.97
#Sta/Elev= 30
  4731.3 1925.16  4824.2 1921.81  4829.6 1922.25  4956.1 1915.77  4961.5 1914.79
  4968.2 1912.37  4988.7 1909.76  4989.1 1909.26  4993.5 1909.76  5023.2 1910.45
  5036.3 1911.62  5080.2 1911.23  5112.8 1912.06  5134.8 1911.65  5206.3 1912.33
  5295.2 1911.82  5393.6 1913.73  5412.6 1914.27  5420.2 1915.03  5430.8 1914.59
  5546.3 1918.42  5628.5 1922.52  5650.4 1924.21  5666.7 1926.34  5716.3 1928.82
  5725.9 1929.99  5760.2 1929.73  5776.5 1930.36  5782.5 1931.44  5850.5 1933.90
#Mann=5,-1,0
  4731.3    0.05       0  4988.7    0.05       0  4993.5    0.05       0
  5393.6    0.12       0  5412.6    0.05       0
Bank Sta=4988.7,4993.5
Exp/Cntr=0.3,0.1

Type RM Length L Ch R = 1,16002,185,185,185
BEGIN DESCRIPTION:
Deadman 36 26.0
END DESCRIPTION:
XS GIS Cut Line= 3
      1666355.01      6898588.04      1666455.00      6899038.00
      1666505.00      6899288.01
#Sta/Elev= 30
  4527.4 1919.29  4537.6 1918.70  4568.3 1917.95  4595.2 1916.80  4619.6 1916.48
  4681.0 1914.78  4692.5 1914.12  4722.0 1913.70  4779.6 1912.06  4784.7 1912.22
  4828.3 1911.21  4871.8 1908.32  4876.9 1908.53  4896.1 1906.31  4906.4 1904.44
  4915.4 1903.56  4947.4 1903.79  4966.7 1903.55  4967.0 1903.05  4971.2 1903.05
  4971.6 1903.55  5080.1 1903.62  5100.5 1904.53  5120.9 1908.07  5141.3 1910.86
  5166.8 1913.33  5212.7 1916.05  5233.1 1918.05  5240.7 1919.10  5243.3 1919.10
#Mann=3,-1,0
  4527.4    0.05       0  4966.7    0.03       0  4971.6    0.05       0
Bank Sta=4966.7,4971.6
Exp/Cntr=0.3,0.1

Type RM Length L Ch R = 1,15817,77,77,77
BEGIN DESCRIPTION:
Mapping XS 9331d461
END DESCRIPTION:
XS GIS Cut Line= 2
      1666120.90      6898452.00      1666437.73      6899398.16
#Sta/Elev= 30
  4232.6 1922.58  4447.4 1916.71  4492.0 1916.41  4542.1 1914.44  4555.3 1914.94
  4671.2 1910.17  4671.5 1909.67  4676.1 1910.17  4736.8 1911.44  4745.1 1910.97
  4755.7 1911.71  4768.3 1915.15  4808.4 1917.52  4871.7 1916.75  4934.9 1917.38
  4952.4 1916.36  4957.7 1917.05  4984.0 1914.75  4989.3 1915.63  4998.2 1915.27
  5015.6 1912.58  5020.8 1915.28  5040.4 1913.56  5047.1 1913.66  5052.4 1915.06
  5078.7 1913.54  5124.8 1917.36  5173.4 1917.96  5205.0 1921.45  5230.4 1922.75
#Mann=3,-1,0
  4232.6    0.05       0  4671.2    0.03       0  4676.1    0.05       0
Bank Sta=4671.2,4676.1
Exp/Cntr=0.3,0.1

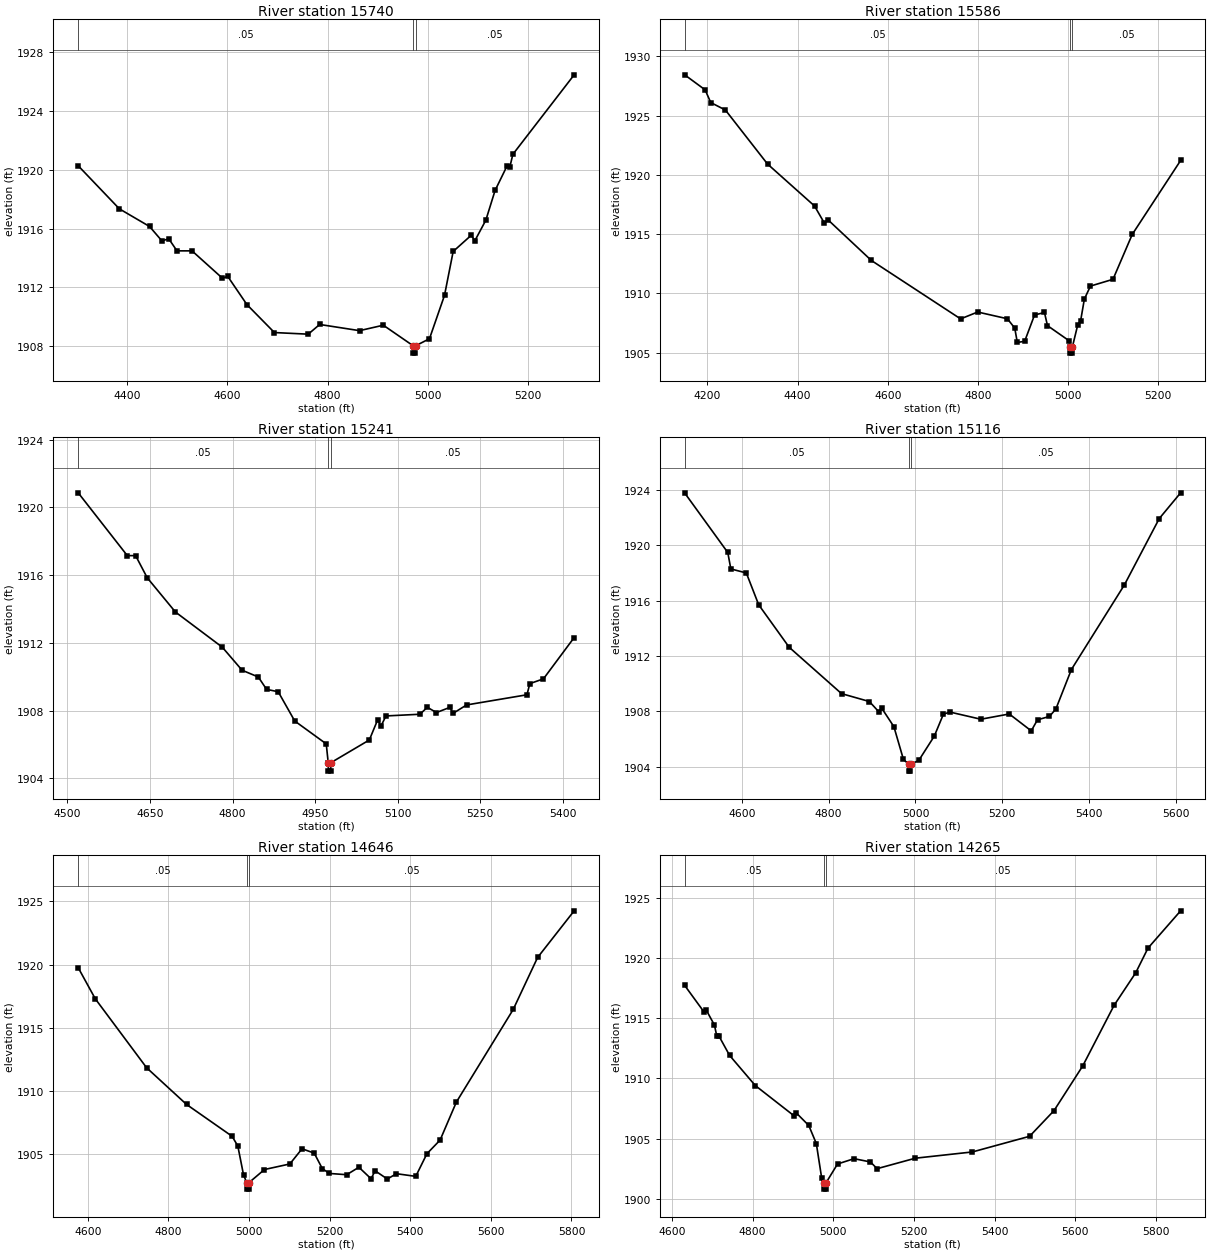
Type RM Length L Ch R = 1,15740,154,154,154
BEGIN DESCRIPTION:
Mapping XS 8e2e5246
END DESCRIPTION:
XS GIS Cut Line= 3
      1666059.60      6898579.23      1666320.51      6899262.69
      1666419.75      6899500.87
#Sta/Elev= 30
  4302.4 1920.28  4384.5 1917.35  4444.7 1916.15  4469.4 1915.17  4483.1 1915.31
  4499.5 1914.49  4529.5 1914.49  4590.1 1912.63  4600.8 1912.75  4639.1 1910.83
  4693.9 1908.93  4761.4 1908.82  4784.2 1909.48  4863.7 1909.06  4911.2 1909.43
  4970.8 1908.03  4971.2 1907.53  4975.4 1907.53  4975.7 1908.03  5003.3 1908.51
  5033.3 1911.46  5050.6 1914.45  5086.6 1915.55  5093.9 1915.18  5115.8 1916.58
  5134.2 1918.60  5158.1 1920.27  5163.5 1920.17  5169.7 1921.06  5292.0 1926.47
#Mann=3,-1,0
  4302.4    0.05       0  4970.8    0.05       0  4975.7    0.05       0
Bank Sta=4970.8,4975.7
Exp/Cntr=0.3,0.1

Type RM Length L Ch R = 1,15586,345,345,345
BEGIN DESCRIPTION:
Deadman 36 25.0
END DESCRIPTION:
XS GIS Cut Line= 3
      1665754.99      6898487.97      1666155.00      6899238.00
      1666304.98      6899437.98
#Sta/Elev= 30
  4149.5 1928.44  4194.9 1927.17  4207.3 1926.10  4239.8 1925.47  4333.3 1920.91
  4437.5 1917.37  4459.4 1915.92  4466.9 1916.22  4563.6 1912.77  4761.5 1907.84
  4799.4 1908.42  4865.3 1907.85  4881.6 1907.06  4887.3 1905.85  4903.6 1905.95
  4925.5 1908.17  4947.5 1908.38  4954.2 1907.27  5002.7 1905.98  5004.4 1905.45
  5004.7 1904.95  5008.9 1904.95  5009.3 1905.45  5021.4 1907.35  5027.7 1907.68
  5036.0 1909.51  5049.5 1910.61  5099.5 1911.18  5142.2 1914.97  5249.5 1921.21
#Mann=3,-1,0
  4149.5    0.05       0  5004.4    0.03       0  5009.3    0.05       0
Bank Sta=5004.4,5009.3
Exp/Cntr=0.3,0.1

Type RM Length L Ch R = 1,15241,125,125,125
BEGIN DESCRIPTION:
Mapping XS 9565bf8a
END DESCRIPTION:
XS GIS Cut Line= 3
      1665580.31      6898749.39      1665892.26      6899222.98
      1666204.19      6899342.08
#Sta/Elev= 30
  4519.5 1920.86  4608.7 1917.15  4623.8 1917.15  4644.9 1915.84  4696.1 1913.82
  4781.3 1911.74  4817.2 1910.38  4846.7 1909.98  4861.7 1909.25  4882.8 1909.11
  4912.9 1907.38  4970.1 1906.03  4973.7 1904.92  4974.0 1904.42  4978.2 1904.42
  4978.6 1904.92  5048.4 1906.26  5063.5 1907.45  5069.5 1907.08  5078.6 1907.68
  5140.2 1907.78  5153.8 1908.19  5170.3 1907.88  5195.0 1908.19  5200.4 1907.83
  5225.1 1908.33  5334.7 1908.93  5340.0 1909.59  5364.7 1909.87  5420.5 1912.31
#Mann=3,-1,0
  4519.5    0.05       0  4973.7    0.05       0  4978.6    0.05       0
Bank Sta=4973.7,4978.6
Exp/Cntr=0.3,0.1

Type RM Length L Ch R = 1,15116,470,470,470
BEGIN DESCRIPTION:
Deadman 36 24.0
END DESCRIPTION:
XS GIS Cut Line= 3
      1665355.00      6898888.00      1665755.00      6899238.00
      1666254.97      6899587.98
#Sta/Elev= 30
  4468.6 1923.78  4567.8 1919.48  4574.9 1918.29  4610.5 1918.00  4639.0 1915.70
  4709.2 1912.63  4829.7 1909.28  4893.8 1908.71  4915.2 1907.98  4921.8 1908.25
  4950.3 1906.89  4972.1 1904.54  4983.9 1904.18  4984.3 1903.68  4988.5 1903.68
  4988.8 1904.18  5007.5 1904.45  5043.3 1906.21  5064.2 1907.79  5079.0 1907.95
  5150.5 1907.43  5215.9 1907.81  5266.5 1906.59  5280.9 1907.39  5308.3 1907.63
  5323.2 1908.17  5358.9 1911.02  5481.0 1917.14  5561.2 1921.93  5610.4 1923.79
#Mann=3,-1,0
  4468.6    0.05       0  4983.9    0.03       0  4988.8    0.05       0
Bank Sta=4983.9,4988.8
Exp/Cntr=0.3,0.1

Type RM Length L Ch R = 1,14646,381,381,381
BEGIN DESCRIPTION:
Deadman 36 23.0
END DESCRIPTION:
XS GIS Cut Line= 3
      1665154.99      6899237.99      1665455.00      6899538.00
      1666255.00      6899638.00
#Sta/Elev= 30
  4576.1 1919.75  4618.5 1917.29  4745.8 1911.84  4844.8 1908.94  4957.9 1906.42
  4972.1 1905.65  4986.2 1903.38  4994.3 1902.74  4994.7 1902.24  4998.9 1902.24
  4999.3 1902.74  5038.2 1903.79  5101.2 1904.23  5131.4 1905.43  5161.6 1905.09
  5181.8 1903.86  5199.4 1903.48  5242.2 1903.38  5272.5 1903.97  5302.7 1903.06
  5312.8 1903.69  5343.0 1903.04  5365.7 1903.46  5413.6 1903.25  5441.3 1905.04
  5474.0 1906.12  5514.3 1909.12  5655.4 1916.45  5715.9 1920.56  5806.6 1924.25
#Mann=3,-1,0
  4576.1    0.05       0  4994.3    0.03       0  4999.3    0.05       0
Bank Sta=4994.3,4999.3
Exp/Cntr=0.3,0.1

Type RM Length L Ch R = 1,14265,509,509,509
BEGIN DESCRIPTION:
Deadman 36 22.0
END DESCRIPTION:
XS GIS Cut Line= 3
      1665054.97      6899988.01      1665424.31      6899866.77
      1666254.96      6899738.01
#Sta/Elev= 30
  4631.6 1917.73  4679.4 1915.53  4684.6 1915.71  4705.3 1914.44  4711.2 1913.52
  4716.4 1913.53  4743.0 1911.91  4806.6 1909.41  4902.1 1906.91  4907.4 1907.16
  4939.2 1906.09  4957.9 1904.59  4971.0 1901.76  4976.4 1901.30  4976.8 1900.80
  4981.1 1900.80  4981.5 1901.30  5010.5 1902.89  5051.4 1903.33  5091.9 1903.06
  5108.6 1902.50  5203.2 1903.37  5344.8 1903.89  5486.5 1905.19  5547.2 1907.33
  5618.1 1911.03  5695.9 1916.07  5749.6 1918.78  5780.0 1920.83  5860.9 1923.93
#Mann=3,-1,0
  4631.6    0.05       0  4976.4    0.03       0  4981.5    0.05       0
Bank Sta=4976.4,4981.5
Exp/Cntr=0.3,0.1

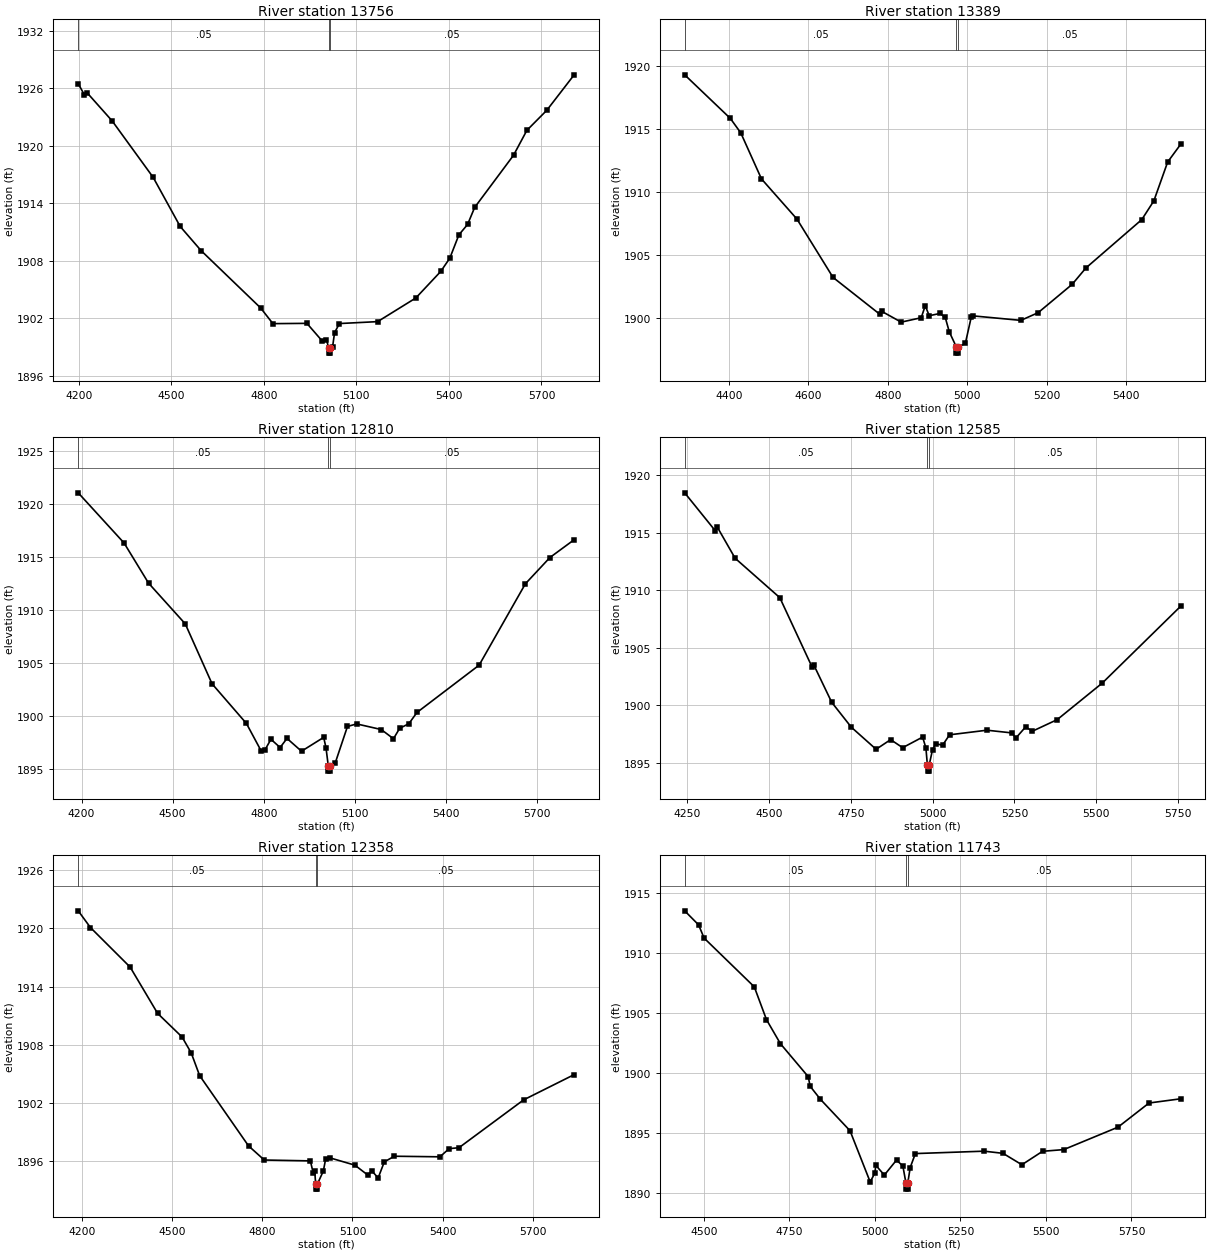
Type RM Length L Ch R = 1,13756,367,367,367
BEGIN DESCRIPTION:
Deadman 36 21.0
END DESCRIPTION:
XS GIS Cut Line= 3
      1664855.01      6900188.00      1665655.00      6900138.00
      1666355.02      6899737.99
#Sta/Elev= 30
  4198.1 1926.50  4218.1 1925.33  4228.2 1925.50  4308.3 1922.60  4441.1 1916.71
  4528.7 1911.58  4596.4 1909.06  4789.2 1903.08  4829.3 1901.43  4939.5 1901.46
  4989.6 1899.60  5002.5 1899.77  5010.8 1898.85  5011.2 1898.35  5015.5 1898.35
  5015.9 1898.85  5022.7 1899.00  5029.2 1900.49  5045.0 1901.44  5168.8 1901.64
  5292.6 1904.11  5373.3 1906.88  5402.8 1908.27  5432.3 1910.71  5460.4 1911.79
  5483.4 1913.57  5609.4 1919.02  5652.6 1921.62  5717.3 1923.72  5805.9 1927.42
#Mann=3,-1,0
  4198.1    0.05       0  5010.8    0.03       0  5015.9    0.05       0
Bank Sta=5010.8,5015.9
Exp/Cntr=0.3,0.1

Type RM Length L Ch R = 1,13389,579,579,579
BEGIN DESCRIPTION:
Deadman 36 20.0
END DESCRIPTION:
XS GIS Cut Line= 3
      1665054.99      6900538.00      1665773.15      6900442.49
      1666254.98      6900238.01
#Sta/Elev= 30
  4288.7 1919.31  4403.6 1915.85  4429.9 1914.70  4481.9 1911.05  4571.2 1907.86
  4662.0 1903.23  4779.9 1900.30  4784.9 1900.53  4833.5 1899.68  4883.9 1900.03
  4894.0 1900.98  4904.1 1900.19  4931.4 1900.37  4944.4 1900.05  4954.5 1898.91
  4972.1 1897.72  4972.5 1897.22  4976.8 1897.22  4977.2 1897.72  4994.9 1897.99
  5009.7 1900.07  5013.2 1900.18  5134.6 1899.82  5178.1 1900.43  5263.7 1902.68
  5298.3 1903.98  5438.9 1907.82  5469.3 1909.31  5504.0 1912.39  5536.6 1913.79
#Mann=3,-1,0
  4288.7    0.05       0  4972.1    0.03       0  4977.2    0.05       0
Bank Sta=4972.1,4977.2
Exp/Cntr=0.3,0.1

Type RM Length L Ch R = 1,12810,225,225,225
BEGIN DESCRIPTION:
Deadman 36 19.0
END DESCRIPTION:
XS GIS Cut Line= 3
      1665005.04      6900837.99      1665805.00      6900738.00
      1666623.92      6900618.33
#Sta/Elev= 30
  4188.9 1921.05  4340.0 1916.31  4420.6 1912.52  4541.6 1908.67  4629.8 1903.01
  4743.1 1899.26  4791.0 1896.70  4803.6 1896.74  4823.8 1897.77  4854.0 1896.99
  4876.7 1897.85  4924.5 1896.64  4997.6 1897.95  5005.2 1896.96  5012.7 1895.26
  5013.1 1894.76  5017.5 1894.76  5017.9 1895.26  5035.5 1895.52  5075.9 1898.98
  5106.3 1899.22  5187.1 1898.69  5227.5 1897.82  5247.7 1898.80  5278.1 1899.24
  5304.8 1900.30  5509.6 1904.77  5662.1 1912.46  5742.9 1914.94  5822.7 1916.62
#Mann=3,-1,0
  4188.9    0.05       0  5012.7    0.03       0  5017.9    0.05       0
Bank Sta=5012.7,5017.9
Exp/Cntr=0.3,0.1

Type RM Length L Ch R = 1,12585,227,227,227
BEGIN DESCRIPTION:
Mapping XS 673b862e
END DESCRIPTION:
XS GIS Cut Line= 3
      1665058.47      6901089.11      1665951.82      6900935.96
      1666550.28      6900823.05
#Sta/Elev= 30
  4242.3 1918.46  4336.4 1915.14  4341.5 1915.50  4396.4 1912.77  4533.0 1909.34
  4631.5 1903.31  4636.6 1903.50  4691.5 1900.24  4751.5 1898.07  4827.2 1896.15
  4871.6 1896.99  4908.4 1896.29  4969.3 1897.21  4979.4 1896.27  4984.0 1894.75
  4984.4 1894.25  4988.8 1894.25  4989.2 1894.75  4999.7 1896.13  5009.9 1896.64
  5030.2 1896.50  5051.7 1897.41  5165.9 1897.81  5243.5 1897.57  5253.7 1897.11
  5284.2 1898.10  5304.6 1897.72  5380.6 1898.73  5518.3 1901.91  5757.7 1908.59
#Mann=3,-1,0
  4242.3    0.05       0  4984.0    0.03       0  4989.2    0.05       0
Bank Sta=4984,4989.2
Exp/Cntr=0.3,0.1

Type RM Length L Ch R = 1,12358,615,615,615
BEGIN DESCRIPTION:
Deadman 36 18.0
END DESCRIPTION:
XS GIS Cut Line= 3
      1665004.98      6901338.00      1665805.00      6901188.00
      1666619.93      6900992.97
#Sta/Elev= 30
  4186.6 1921.81  4227.3 1920.09  4359.6 1916.01  4451.1 1911.24  4532.5 1908.81
  4563.1 1907.16  4591.0 1904.83  4753.8 1897.59  4806.4 1896.13  4959.9 1896.04
  4969.2 1894.81  4974.3 1895.01  4977.6 1893.63  4978.0 1893.13  4982.5 1893.13
  4982.9 1893.63  5003.1 1895.00  5010.8 1896.24  5024.2 1896.36  5108.2 1895.60
  5150.3 1894.60  5165.1 1895.00  5185.6 1894.28  5206.2 1895.94  5239.5 1896.52
  5391.3 1896.46  5422.1 1897.30  5454.9 1897.40  5670.3 1902.33  5838.5 1904.93
#Mann=3,-1,0
  4186.6    0.05       0  4977.6    0.03       0  4982.9    0.05       0
Bank Sta=4977.6,4982.9
Exp/Cntr=0.3,0.1

Type RM Length L Ch R = 1,11743,861,861,861
BEGIN DESCRIPTION:
Deadman 36 17.0
END DESCRIPTION:
XS GIS Cut Line= 3
      1665179.97      6901813.01      1665718.31      6901674.36
      1666554.89      6901360.00
#Sta/Elev= 30
  4444.1 1913.52  4484.8 1912.35  4500.9 1911.25  4647.6 1907.19  4683.2 1904.46
  4723.9 1902.46  4805.3 1899.71  4810.7 1898.92  4840.8 1897.83  4927.4 1895.21
  4986.3 1890.95  5000.0 1891.69  5002.8 1892.33  5027.7 1891.52  5063.3 1892.77
  5081.9 1892.27  5090.9 1890.85  5091.3 1890.35  5095.8 1890.35  5096.2 1890.85
  5103.3 1892.15  5118.4 1893.31  5319.4 1893.51  5374.6 1893.33  5429.7 1892.38
  5490.2 1893.50  5552.0 1893.64  5710.7 1895.51  5801.4 1897.52  5893.7 1897.87
#Mann=3,-1,0
  4444.1    0.05       0  5090.9    0.03       0  5096.2    0.05       0
Bank Sta=5090.9,5096.2
Exp/Cntr=0.3,0.1

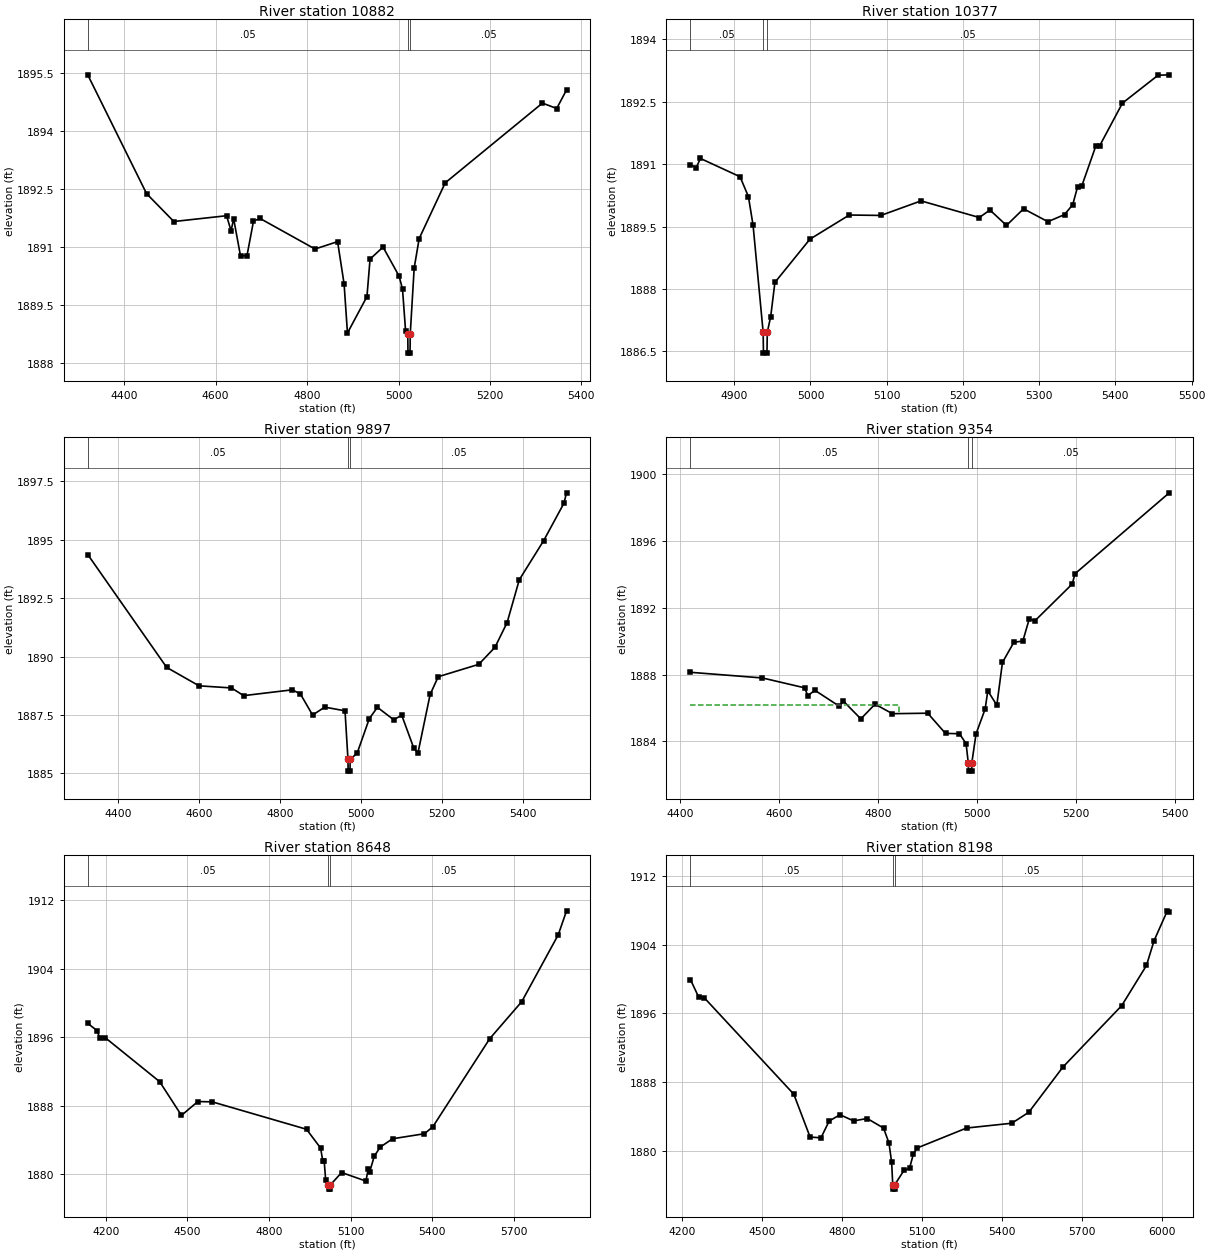
Type RM Length L Ch R = 1,10882,505,505,505
BEGIN DESCRIPTION:
Mapping XS 1ccdf36d
END DESCRIPTION:
XS GIS Cut Line= 4
      1665588.78      6902115.77      1665878.08      6901956.94
      1666136.16      6901670.50      1666455.86      6901582.80
#Sta/Elev= 30
  4320.4 1895.45  4449.1 1892.38  4508.7 1891.66  4624.1 1891.81  4633.8 1891.42
  4639.5 1891.73  4654.5 1890.77  4668.7 1890.78  4682.9 1891.67  4697.1 1891.74
  4817.4 1890.95  4866.8 1891.14  4881.0 1890.05  4888.4 1888.78  4931.0 1889.72
  4937.8 1890.69  4966.2 1891.00  5001.3 1890.25  5008.8 1889.91  5015.5 1888.83
  5020.3 1888.76  5020.7 1888.26  5025.2 1888.26  5025.7 1888.76  5034.3 1890.46
  5045.2 1891.22  5102.2 1892.66  5314.8 1894.72  5345.9 1894.58  5367.5 1895.06
#Mann=3,-1,0
  4320.4    0.05       0  5020.3    0.03       0  5025.7    0.05       0
Bank Sta=5020.3,5025.7
Exp/Cntr=0.3,0.1

Type RM Length L Ch R = 1,10377,480,480,480
BEGIN DESCRIPTION:
Mapping XS 4c268566
END DESCRIPTION:
XS GIS Cut Line= 3
      1665825.80      6902067.43      1666025.41      6901976.30
      1666401.48      6901816.37
#Sta/Elev= 30
  4842.5 1890.99  4850.1 1890.92  4855.6 1891.14  4907.6 1890.70  4918.6 1890.22
  4924.7 1889.53  4937.9 1886.96  4938.3 1886.46  4942.9 1886.46  4943.3 1886.96
  4947.8 1887.34  4953.3 1888.16  4999.3 1889.20  5050.9 1889.78  5092.3 1889.77
  5145.0 1890.12  5221.4 1889.72  5235.4 1889.90  5257.1 1889.53  5279.5 1889.93
  5311.4 1889.62  5333.2 1889.79  5344.0 1890.03  5350.4 1890.46  5355.9 1890.48
  5374.1 1891.43  5379.5 1891.45  5409.2 1892.47  5455.9 1893.14  5470.6 1893.15
#Mann=3,-1,0
  4842.5    0.05       0  4937.9    0.05       0  4943.3    0.05       0
Bank Sta=4937.9,4943.3
Exp/Cntr=0.3,0.1

Type RM Length L Ch R = 1,9897,543,543,543
BEGIN DESCRIPTION:
Mapping XS 443cb642
END DESCRIPTION:
XS GIS Cut Line= 2
      1665580.26      6902232.04      1666761.63      6902223.71
#Sta/Elev= 30
  4325.6 1894.37  4520.3 1889.54  4600.3 1888.75  4680.3 1888.66  4710.3 1888.33
  4830.4 1888.58  4850.4 1888.40  4880.4 1887.50  4910.4 1887.84  4960.4 1887.68
  4967.7 1885.60  4968.1 1885.10  4972.7 1885.10  4973.1 1885.60  4990.4 1885.87
  5020.4 1887.35  5040.4 1887.83  5080.4 1887.30  5100.4 1887.49  5130.4 1886.07
  5140.4 1885.88  5170.4 1888.38  5190.4 1889.14  5290.4 1889.67  5330.4 1890.40
  5360.4 1891.46  5390.4 1893.29  5450.4 1894.96  5500.4 1896.56  5507.0 1897.01
#Mann=3,-1,0
  4325.6    0.05       0  4967.7    0.05       0  4973.1    0.05       0
Bank Sta=4967.7,4973.1
Exp/Cntr=0.3,0.1

Type RM Length L Ch R = 1,9354,706,706,706
BEGIN DESCRIPTION:
Deadman 36 16.0
END DESCRIPTION:
XS GIS Cut Line= 3
      1665951.64      6902267.11      1666402.09      6902630.10
      1666555.00      6902988.00
#Sta/Elev= 30
  4421.5 1888.14  4567.1 1887.80  4652.3 1887.21  4658.7 1886.74  4673.1 1887.06
  4722.7 1886.10  4730.7 1886.41  4765.9 1885.35  4794.6 1886.23  4829.8 1885.66
  4901.0 1885.69  4937.0 1884.48  4965.2 1884.46  4978.6 1883.87  4983.0 1882.72
  4983.5 1882.22  4989.7 1882.22  4990.2 1882.72  4998.7 1884.45  5017.1 1885.94
  5022.5 1887.03  5040.7 1886.17  5052.1 1888.73  5075.2 1889.94  5093.3 1890.01
  5106.5 1891.36  5116.9 1891.20  5193.2 1893.43  5198.6 1894.04  5389.2 1898.89
#Mann=3,-1,0
  4421.5    0.05       0  4983.0    0.05       0  4990.2    0.05       0
#XS Ineff=2,0
    0.00 4843.60 1886.17               0
Permanent Ineff=
       F       F
Bank Sta=4983,4990.2
Exp/Cntr=0.3,0.1

Type RM Length L Ch R = 1,8648,450,450,450
BEGIN DESCRIPTION:
Deadman 36 15.0
END DESCRIPTION:
XS GIS Cut Line= 3
      1665041.47      6902714.17      1665905.00      6902788.00
      1666704.99      6903188.00
#Sta/Elev= 30
  4133.3 1897.62  4167.0 1896.78  4177.0 1895.96  4197.1 1895.96  4397.8 1890.81
  4478.1 1886.87  4538.3 1888.49  4591.3 1888.45  4938.0 1885.25  4989.9 1883.05
  4997.5 1881.60  5002.8 1881.60  5008.4 1879.35  5018.7 1878.76  5019.2 1878.26
  5025.5 1878.26  5026.0 1878.76  5067.1 1880.20  5156.5 1879.20  5164.9 1880.59
  5170.5 1880.29  5187.3 1882.12  5209.6 1883.18  5254.3 1884.14  5371.7 1884.73
  5402.5 1885.54  5612.1 1895.84  5729.5 1900.15  5863.7 1907.95  5894.4 1910.76
#Mann=3,-1,0
  4133.3    0.05       0  5018.7    0.05       0  5026.0    0.05       0
Bank Sta=5018.7,5026
Exp/Cntr=0.3,0.1

Type RM Length L Ch R = 1,8198,430,430,430
BEGIN DESCRIPTION:
Deadman 36 14.0
END DESCRIPTION:
XS GIS Cut Line= 3
      1664954.95      6902987.99      1665705.00      6903138.00
      1666505.02      6903788.01
#Sta/Elev= 30
  4230.2 1899.93  4260.8 1897.91  4281.2 1897.84  4617.8 1886.59  4679.0 1881.60
  4719.8 1881.51  4750.3 1883.46  4791.1 1884.20  4842.1 1883.48  4893.1 1883.76
  4954.3 1882.65  4974.7 1880.92  4984.9 1878.65  4988.9 1876.04  4989.4 1875.54
  4995.7 1875.54  4996.2 1876.04  5031.0 1877.72  5051.8 1877.95  5066.2 1879.62
  5080.6 1880.33  5265.7 1882.65  5435.4 1883.21  5499.3 1884.49  5627.2 1889.75
  5847.7 1896.90  5940.4 1901.57  5969.1 1904.47  6018.7 1907.93  6025.9 1907.85
#Mann=3,-1,0
  4230.2    0.05       0  4988.9    0.03       0  4996.2    0.05       0
Bank Sta=4988.9,4996.2
Exp/Cntr=0.3,0.1