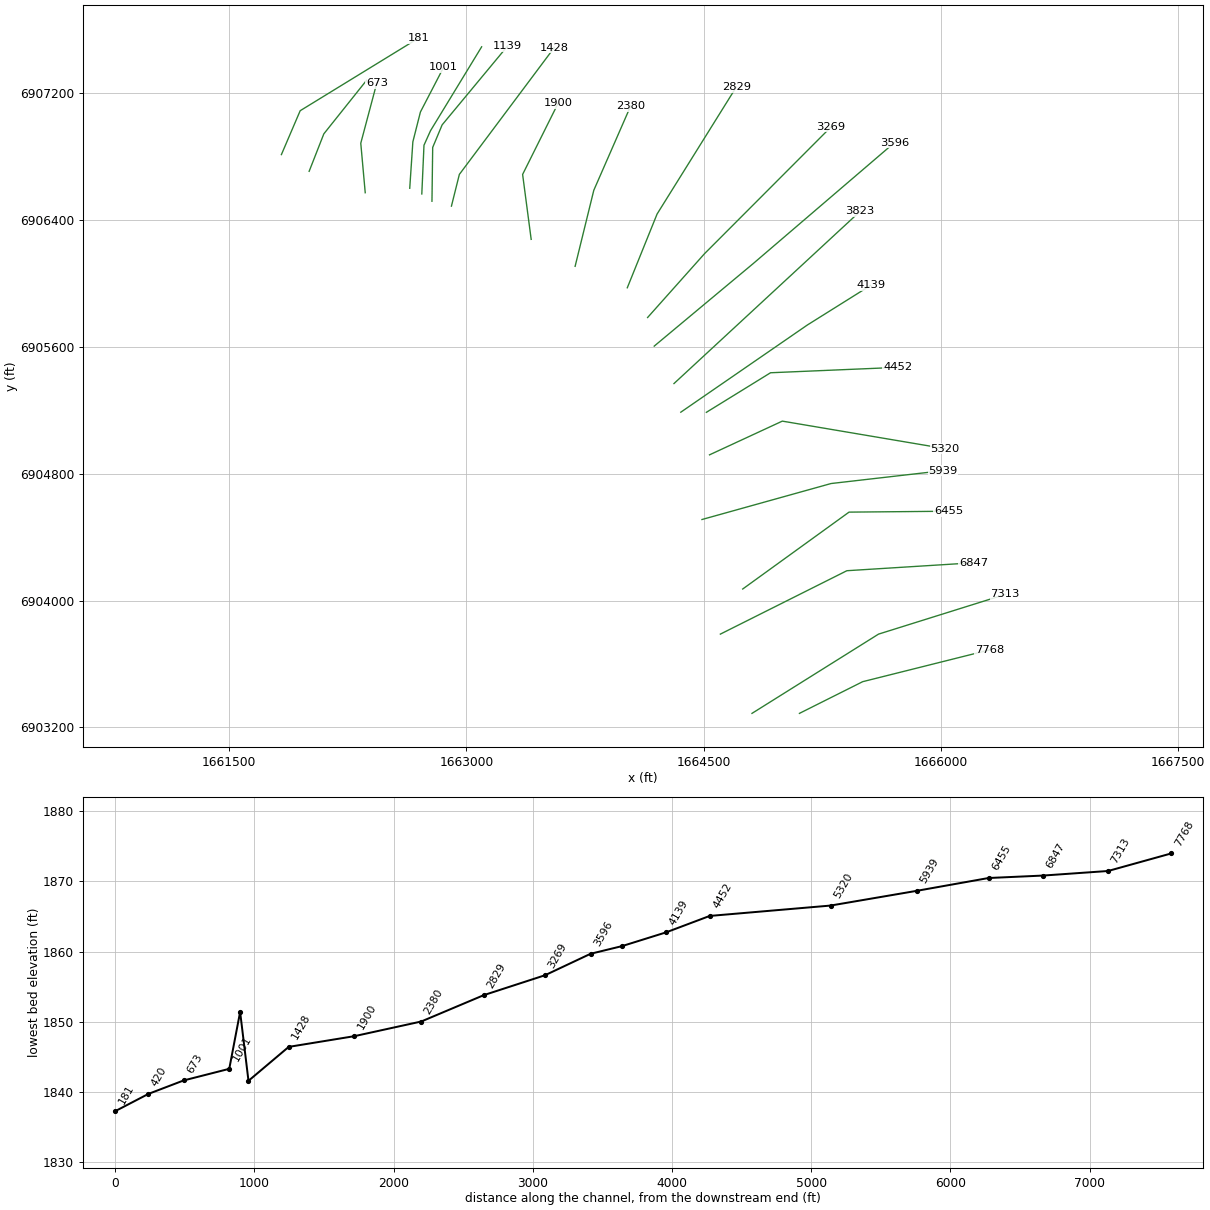
HEC-RAS study Deadman 36.prj: Deadman 36 Base Level Engineering

--- Deadman 36.g01 (geometry) --- (continued)

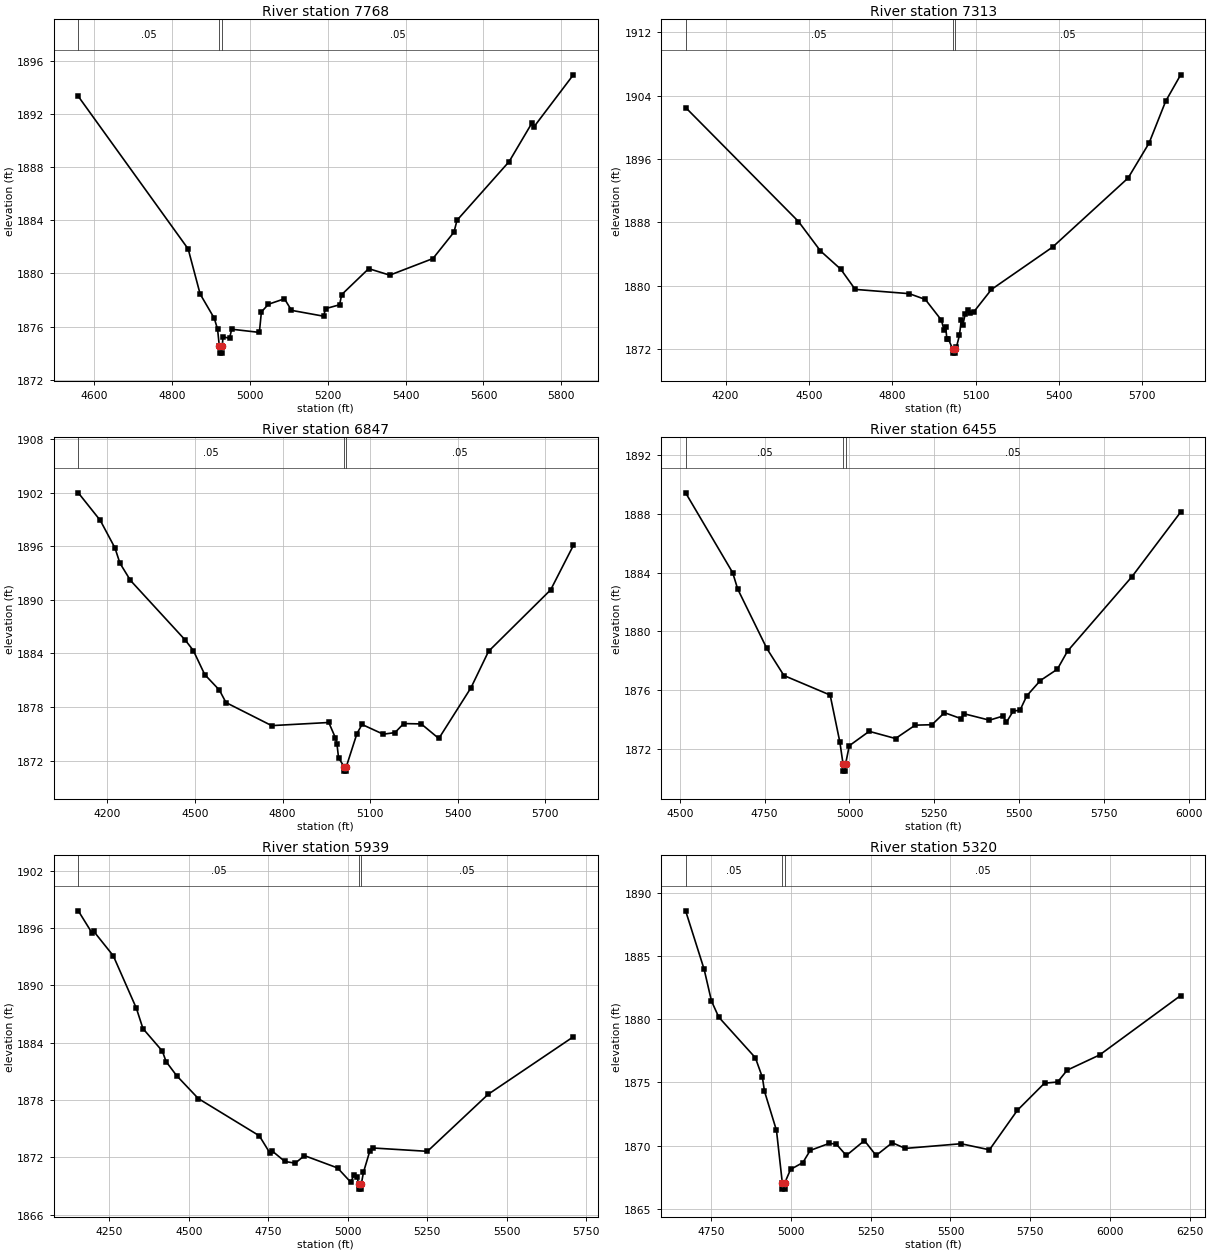
Type RM Length L Ch R = 1,7768,455,455,455
BEGIN DESCRIPTION:
Deadman 36 13.0
END DESCRIPTION:
XS GIS Cut Line= 3
      1665105.01      6903288.01      1665505.00      6903488.00
      1666304.98      6903687.99
#Sta/Elev= 30
  4559.1 1893.33  4841.4 1881.84  4872.1 1878.45  4908.5 1876.62  4916.9 1875.80
  4921.5 1874.50  4922.0 1874.00  4928.5 1874.00  4929.0 1874.50  4930.8 1875.24
  4947.6 1875.11  4953.2 1875.80  5024.3 1875.56  5029.5 1877.10  5047.5 1877.68
  5088.8 1878.09  5106.8 1877.22  5189.3 1876.78  5194.4 1877.35  5230.5 1877.64
  5235.6 1878.40  5305.2 1880.36  5359.3 1879.87  5470.2 1881.12  5524.3 1883.11
  5532.0 1884.00  5666.0 1888.42  5725.3 1891.36  5730.4 1891.06  5830.9 1894.95
#Mann=3,-1,0
  4559.1    0.05       0  4921.5    0.03       0  4929.0    0.05       0
Bank Sta=4921.5,4929
Exp/Cntr=0.3,0.1

Type RM Length L Ch R = 1,7313,466,466,466
BEGIN DESCRIPTION:
Deadman 36 12.0
END DESCRIPTION:
XS GIS Cut Line= 3
      1664805.03      6903288.02      1665605.00      6903788.00
      1666404.99      6904038.00
#Sta/Elev= 30
  4056.1 1902.51  4462.3 1888.11  4541.3 1884.40  4614.4 1882.09  4666.3 1879.54
  4860.9 1879.00  4918.7 1878.27  4976.5 1875.66  4985.9 1874.41  4991.8 1874.77
  4996.5 1873.25  5002.1 1873.25  5017.1 1871.99  5017.6 1871.49  5024.2 1871.49
  5024.7 1871.99  5030.9 1872.28  5041.4 1873.73  5048.2 1875.65  5053.4 1874.99
  5062.3 1876.45  5072.8 1876.96  5080.7 1876.52  5093.8 1876.73  5156.6 1879.53
  5376.6 1884.88  5648.5 1893.61  5723.9 1898.02  5783.7 1903.31  5837.6 1906.64
#Mann=3,-1,0
  4056.1    0.05       0  5017.1    0.03       0  5024.7    0.05       0
Bank Sta=5017.1,5024.7
Exp/Cntr=0.3,0.1

Type RM Length L Ch R = 1,6847,392,392,392
BEGIN DESCRIPTION:
Deadman 36 11.0
END DESCRIPTION:
XS GIS Cut Line= 3
      1664605.03      6903788.02      1665405.00      6904188.00
      1666204.95      6904238.00
#Sta/Elev= 30
  4100.0 1901.97  4175.4 1898.88  4225.7 1895.80  4242.5 1894.11  4278.8 1892.17
  4466.1 1885.51  4494.1 1884.33  4533.2 1881.64  4583.5 1879.90  4605.9 1878.51
  4762.4 1875.93  4958.1 1876.28  4980.4 1874.60  4986.0 1873.92  4991.6 1872.33
  5010.6 1871.34  5011.1 1870.84  5017.7 1870.84  5018.2 1871.34  5054.5 1875.03
  5072.0 1876.06  5144.7 1874.97  5184.8 1875.15  5214.8 1876.16  5274.9 1876.12
  5335.1 1874.49  5445.3 1880.17  5505.4 1884.24  5718.3 1891.12  5795.9 1896.08
#Mann=3,-1,0
  4100.0    0.05       0  5010.6    0.03       0  5018.2    0.05       0
Bank Sta=5010.6,5018.2
Exp/Cntr=0.3,0.1

Type RM Length L Ch R = 1,6455,516,516,516
BEGIN DESCRIPTION:
Mapping XS a2182d5e
END DESCRIPTION:
XS GIS Cut Line= 3
      1664746.46      6904072.62      1665418.64      6904557.61
      1666048.24      6904563.28
#Sta/Elev= 30
  4517.3 1889.44  4656.0 1884.00  4670.7 1882.89  4756.6 1878.84  4806.9 1877.00
  4943.1 1875.67  4971.8 1872.46  4981.0 1870.99  4981.5 1870.49  4988.2 1870.49
  4988.7 1870.99  4999.5 1872.22  5058.1 1873.20  5135.7 1872.71  5193.7 1873.62
  5243.0 1873.65  5280.0 1874.47  5329.4 1874.06  5336.9 1874.40  5412.5 1873.96
  5452.5 1874.24  5462.5 1873.82  5482.5 1874.58  5502.5 1874.64  5522.5 1875.62
  5562.5 1876.66  5612.5 1877.43  5642.5 1878.66  5832.6 1883.74  5975.8 1888.13
#Mann=3,-1,0
  4517.3    0.05       0  4981.0    0.03       0  4988.7    0.05       0
Bank Sta=4981,4988.7
Exp/Cntr=0.3,0.1

Type RM Length L Ch R = 1,5939,619,619,619
BEGIN DESCRIPTION:
Deadman 36 10.0
END DESCRIPTION:
XS GIS Cut Line= 3
      1664488.91      6904511.02      1665305.00      6904738.00
      1666011.20      6904819.05
#Sta/Elev= 30
  4152.2 1897.82  4195.9 1895.47  4201.1 1895.66  4262.3 1893.11  4335.0 1887.61
  4355.7 1885.48  4416.8 1883.12  4428.4 1882.03  4461.4 1880.56  4529.9 1878.15
  4721.8 1874.25  4756.0 1872.40  4761.2 1872.69  4802.1 1871.56  4834.9 1871.38
  4863.9 1872.17  4968.1 1870.88  5009.3 1869.40  5019.4 1870.09  5029.5 1869.92
  5034.9 1869.16  5035.4 1868.66  5042.2 1868.66  5042.7 1869.16  5049.6 1870.42
  5069.7 1872.66  5079.8 1872.97  5250.9 1872.62  5442.2 1878.60  5710.1 1884.62
#Mann=3,-1,0
  4152.2    0.05       0  5034.9    0.03       0  5042.7    0.05       0
Bank Sta=5034.9,5042.7
Exp/Cntr=0.3,0.1

Type RM Length L Ch R = 1,5320,868,868,868
BEGIN DESCRIPTION:
Deadman 36 9.0
END DESCRIPTION:
XS GIS Cut Line= 3
      1664536.71      6904919.02      1664996.76      6905131.69
      1666025.39      6904958.08
#Sta/Elev= 30
  4670.8 1888.57  4728.7 1883.95  4751.7 1881.44  4774.6 1880.16  4889.2 1876.95
  4911.3 1875.39  4917.7 1874.30  4955.3 1871.20  4973.5 1867.06  4974.0 1866.56
  4980.8 1866.56  4981.3 1867.06  4999.4 1868.12  5037.9 1868.66  5060.8 1869.62
  5120.6 1870.18  5142.6 1870.12  5173.9 1869.22  5230.7 1870.40  5267.1 1869.22
  5317.8 1870.23  5358.4 1869.78  5533.1 1870.15  5622.1 1869.67  5709.4 1872.79
  5794.5 1874.94  5835.4 1875.03  5865.5 1875.97  5966.9 1877.17  6220.8 1881.87
#Mann=3,-1,0
  4670.8    0.05       0  4973.5    0.03       0  4981.3    0.05       0
Bank Sta=4973.5,4981.3
Exp/Cntr=0.3,0.1

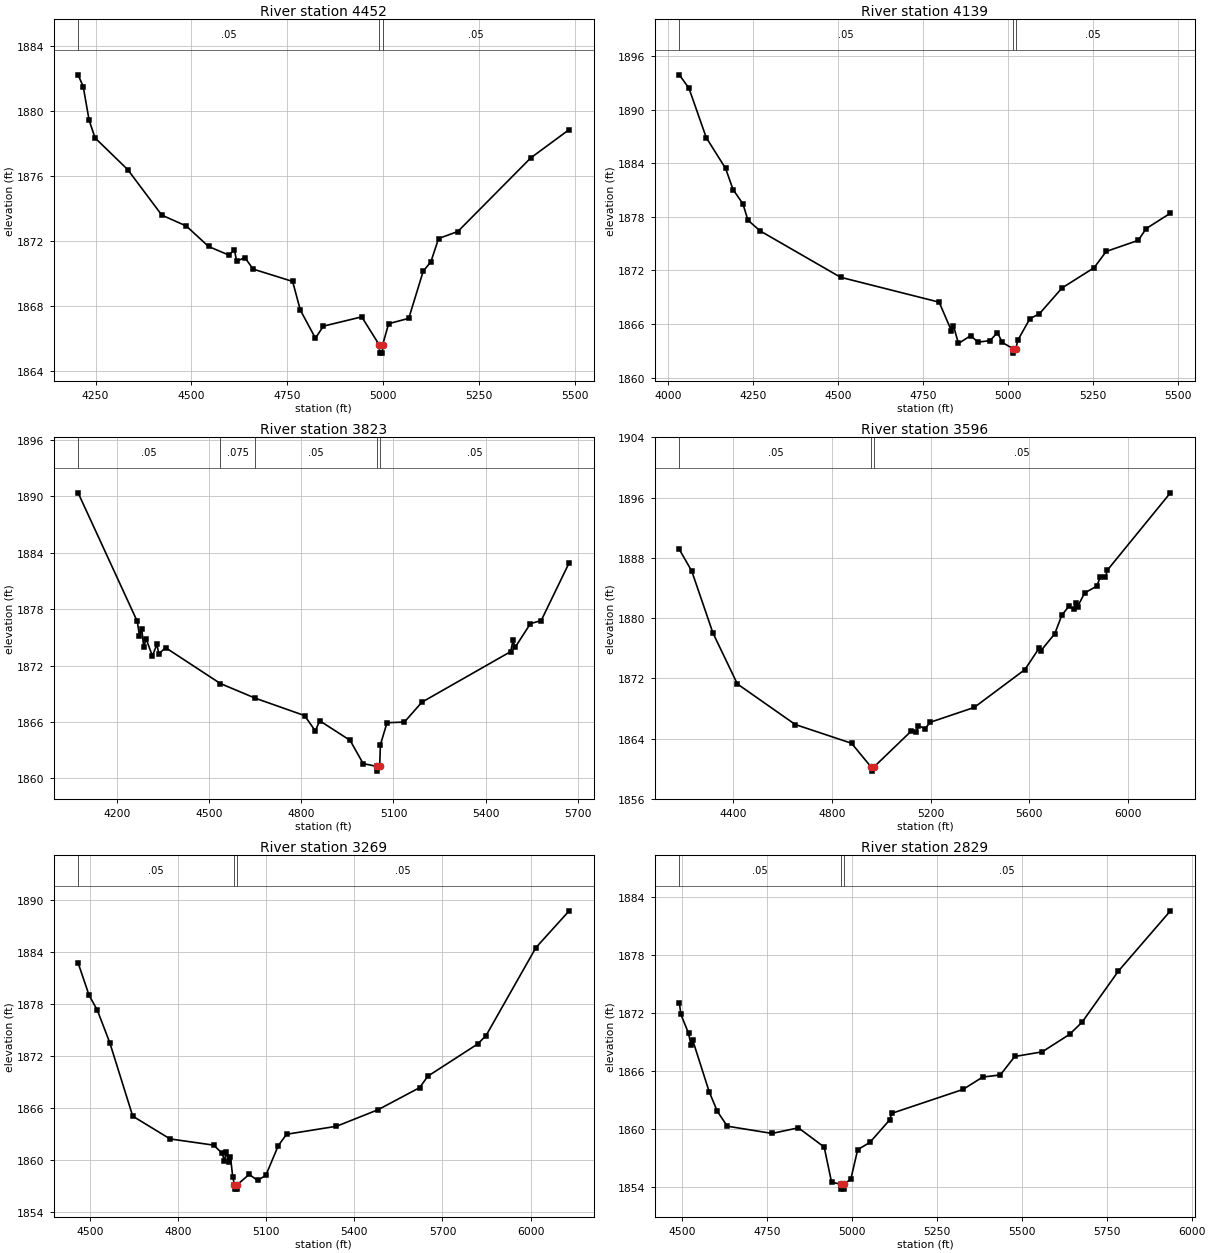
Type RM Length L Ch R = 1,4452,313,313,313
BEGIN DESCRIPTION:
Mapping XS 4ec7d040
END DESCRIPTION:
XS GIS Cut Line= 3
      1664516.74      6905187.20      1664922.33      6905436.79
      1665724.97      6905470.82
#Sta/Elev= 30
  4204.6 1882.20  4217.9 1881.48  4233.3 1879.41  4248.7 1878.32  4333.9 1876.37
  4422.7 1873.57  4486.5 1872.90  4544.5 1871.64  4596.6 1871.12  4612.0 1871.41
  4617.9 1870.73  4639.2 1870.96  4660.5 1870.25  4763.6 1869.49  4783.6 1867.73
  4823.0 1866.00  4843.7 1866.74  4943.7 1867.31  4989.5 1865.58  4990.0 1865.08
  4997.5 1865.08  4998.0 1865.58  5013.8 1866.89  5066.2 1867.22  5103.9 1870.12
  5123.9 1870.70  5143.9 1872.13  5194.0 1872.56  5384.1 1877.09  5484.2 1878.83
#Mann=3,-1,0
  4204.6    0.05       0  4989.5    0.03       0  4998.0    0.05       0
Bank Sta=4989.5,4998
Exp/Cntr=0.3,0.1

Type RM Length L Ch R = 1,4139,316,316,316
BEGIN DESCRIPTION:
Deadman 36 8.0
END DESCRIPTION:
XS GIS Cut Line= 3
      1664355.02      6905188.01      1665155.00      6905738.00
      1665555.00      6905988.00
#Sta/Elev= 30
  4034.0 1893.92  4062.4 1892.40  4113.1 1886.88  4169.9 1883.43  4191.7 1881.07
  4220.7 1879.47  4235.6 1877.63  4271.4 1876.43  4507.5 1871.24  4797.1 1868.45
  4833.0 1865.26  4839.0 1865.82  4853.9 1863.82  4889.8 1864.70  4910.8 1863.97
  4946.6 1864.14  4968.4 1865.04  4982.5 1863.94  5014.1 1863.24  5014.6 1862.74
  5022.7 1863.24  5027.8 1864.16  5063.8 1866.60  5091.5 1867.14  5158.1 1870.04
  5252.4 1872.31  5287.8 1874.13  5382.2 1875.38  5405.2 1876.69  5476.5 1878.42
#Mann=3,-1,0
  4034.0    0.05       0  5014.1    0.05       0  5022.7    0.05       0
Bank Sta=5014.1,5022.7
Exp/Cntr=0.3,0.1

Type RM Length L Ch R = 1,3823,227,227,227
BEGIN DESCRIPTION:
Mapping XS c7cfc652
END DESCRIPTION:
XS GIS Cut Line= 2
      1664311.88      6905368.67      1665487.65      6906454.27
#Sta/Elev= 30
  4072.2 1890.39  4265.2 1876.70  4272.0 1875.21  4279.4 1875.92  4286.2 1873.96
  4293.6 1874.87  4314.5 1873.02  4328.7 1874.26  4335.5 1873.26  4357.1 1873.92
  4535.8 1870.10  4649.7 1868.54  4810.1 1866.69  4845.3 1865.06  4859.5 1866.14
  4958.7 1864.05  5001.2 1861.58  5046.2 1861.28  5046.7 1860.78  5054.9 1861.28
  5057.4 1863.60  5078.9 1865.93  5135.6 1866.00  5192.3 1868.11  5482.1 1873.50
  5489.4 1874.70  5496.2 1873.94  5546.1 1876.47  5581.3 1876.80  5672.5 1882.95
#Mann=5,-1,0
  4072.2    0.05       0  4535.8   0.075       0  4649.7    0.05       0
  5046.2    0.05       0  5054.9    0.05       0
Bank Sta=5046.2,5054.9
Exp/Cntr=0.3,0.1

Type RM Length L Ch R = 1,3596,327,327,327
BEGIN DESCRIPTION:
Deadman 36 7.0
END DESCRIPTION:
XS GIS Cut Line= 3
      1664186.90      6905604.80      1664814.67      6906127.20
      1665704.99      6906887.99
#Sta/Elev= 30
  4183.3 1889.13  4233.4 1886.26  4319.3 1878.03  4418.2 1871.26  4652.6 1865.87
  4880.4 1863.38  4960.7 1860.18  4961.2 1859.68  4969.4 1860.18  5121.0 1864.97
  5143.0 1864.91  5149.6 1865.71  5178.1 1865.34  5199.0 1866.17  5376.8 1868.14
  5582.1 1873.17  5639.2 1876.00  5645.8 1875.63  5702.9 1877.93  5731.4 1880.38
  5760.0 1881.58  5780.8 1881.19  5788.5 1882.08  5795.1 1881.51  5823.7 1883.35
  5873.0 1884.25  5887.3 1885.47  5908.2 1885.43  5915.9 1886.38  6171.1 1896.65
#Mann=3,-1,0
  4183.3    0.05       0  4960.7    0.03       0  4969.4    0.05       0
Bank Sta=4960.7,4969.4
Exp/Cntr=0.3,0.1

Type RM Length L Ch R = 1,3269,440,440,440
BEGIN DESCRIPTION:
Deadman 36 6.0
END DESCRIPTION:
XS GIS Cut Line= 3
      1664145.21      6905785.34      1664505.00      6906188.00
      1665305.03      6906988.03
#Sta/Elev= 30
  4459.9 1882.76  4497.1 1879.03  4525.5 1877.28  4568.1 1873.50  4645.9 1865.05
  4772.9 1862.42  4921.7 1861.70  4950.2 1860.75  4957.7 1859.92  4964.4 1860.87
  4971.9 1859.72  4978.6 1860.33  4986.1 1858.06  4992.1 1857.12  4992.6 1856.62
  5000.4 1856.62  5000.9 1857.12  5042.3 1858.32  5070.6 1857.63  5098.9 1858.21
  5141.3 1861.65  5169.6 1862.96  5339.3 1863.88  5480.7 1865.79  5622.1 1868.34
  5650.4 1869.67  5820.1 1873.39  5848.4 1874.36  6018.1 1884.52  6131.3 1888.77
#Mann=3,-1,0
  4459.9    0.05       0  4992.1    0.05       0  5000.9    0.05       0
Bank Sta=4992.1,5000.9
Exp/Cntr=0.3,0.1

Type RM Length L Ch R = 1,2829,449,449,449
BEGIN DESCRIPTION:
Deadman 36 5.0
END DESCRIPTION:
XS GIS Cut Line= 3
      1664016.71      6905972.80      1664205.00      6906438.00
      1664705.02      6907238.03
#Sta/Elev= 30
  4492.2 1873.10  4496.7 1871.88  4519.4 1869.92  4526.2 1868.73  4531.6 1869.21
  4579.8 1863.89  4603.9 1861.84  4633.4 1860.30  4764.8 1859.55  4842.6 1860.13
  4918.5 1858.14  4940.1 1854.51  4968.0 1854.28  4968.5 1853.78  4976.4 1853.78
  4976.9 1854.28  4997.0 1854.83  5017.1 1857.87  5053.0 1858.62  5111.4 1860.96
  5117.3 1861.63  5327.2 1864.11  5385.0 1865.39  5436.9 1865.61  5479.3 1867.52
  5560.1 1868.00  5640.9 1869.82  5677.4 1871.07  5784.2 1876.36  5937.5 1882.61
#Mann=3,-1,0
  4492.2    0.05       0  4968.0    0.05       0  4976.9    0.05       0
Bank Sta=4968,4976.9
Exp/Cntr=0.3,0.1

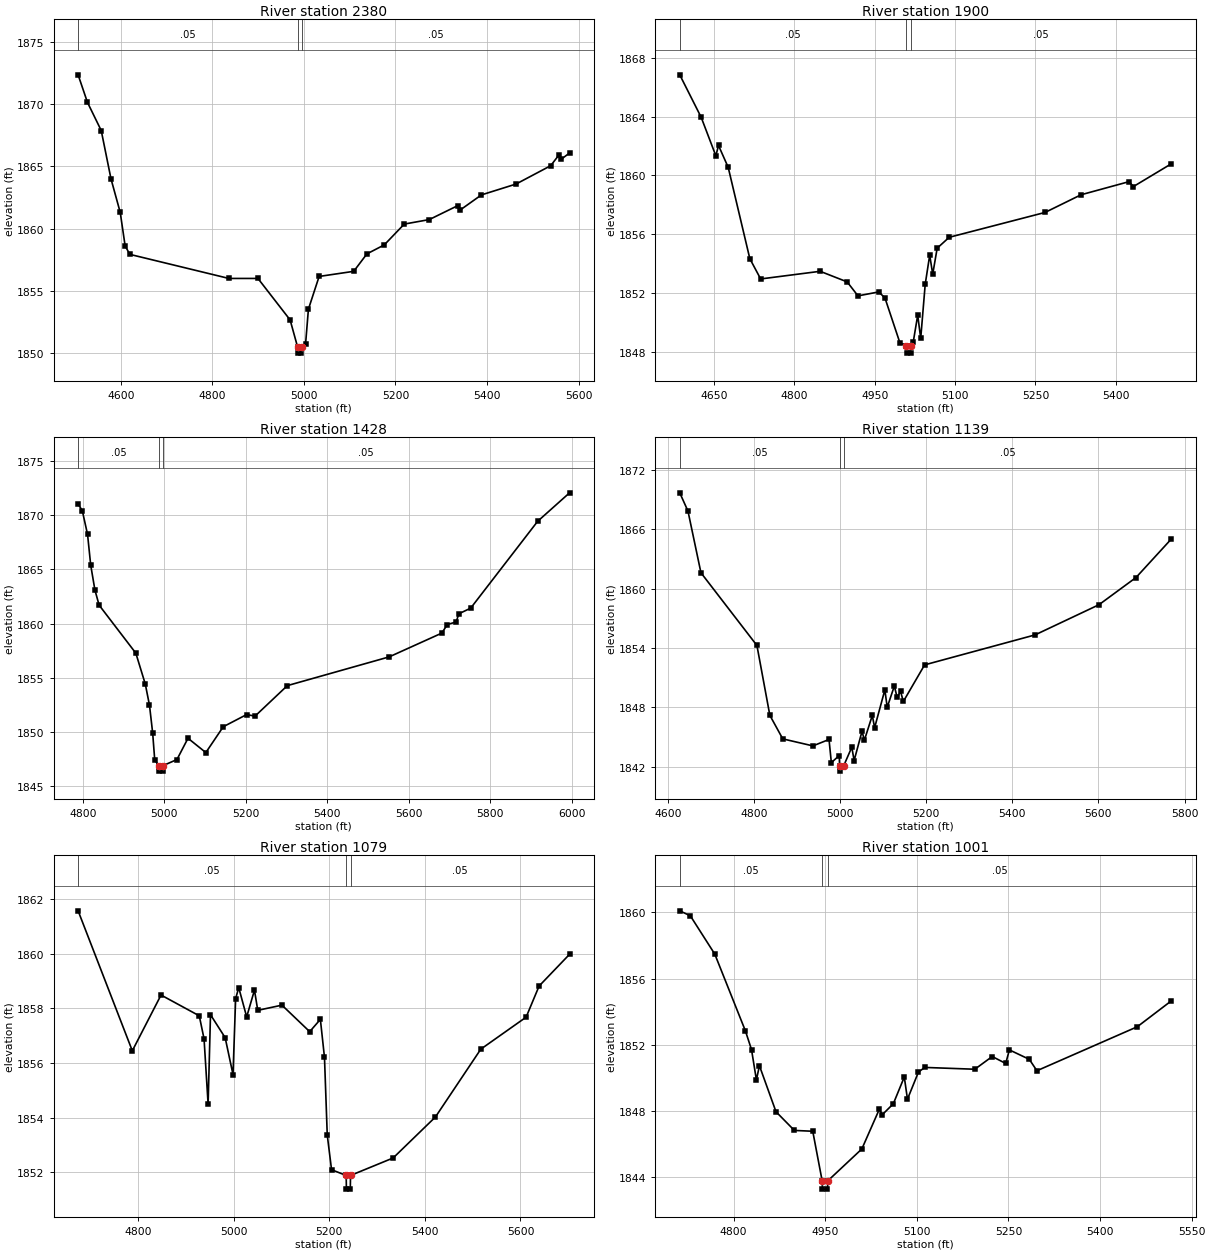
Type RM Length L Ch R = 1,2380,480,480,480
BEGIN DESCRIPTION:
Deadman 36 4.0
END DESCRIPTION:
XS GIS Cut Line= 3
      1663686.88      6906108.29      1663805.00      6906588.00
      1664037.55      6907118.64
#Sta/Elev= 30
  4507.0 1872.34  4527.3 1870.14  4557.5 1867.87  4578.8 1864.00  4599.0 1861.30
  4609.7 1858.62  4620.0 1857.94  4836.3 1856.01  4899.8 1856.01  4970.1 1852.68
  4986.3 1850.52  4986.8 1850.02  4994.7 1850.02  4995.2 1850.52  5003.8 1850.75
  5010.0 1853.54  5033.4 1856.17  5109.0 1856.58  5137.8 1857.98  5175.7 1858.70
  5219.4 1860.37  5274.0 1860.73  5335.7 1861.84  5341.2 1861.49  5387.9 1862.71
  5463.5 1863.58  5539.1 1865.05  5557.0 1865.90  5562.5 1865.58  5580.4 1866.07
#Mann=3,-1,0
  4507.0    0.05       0  4986.3    0.03       0  4995.2    0.05       0
Bank Sta=4986.3,4995.2
Exp/Cntr=0.3,0.1

Type RM Length L Ch R = 1,1900,472,472,472
BEGIN DESCRIPTION:
Deadman 36 3.0
END DESCRIPTION:
XS GIS Cut Line= 3
      1663409.09      6906278.39      1663355.00      6906688.00
      1663580.23      6907138.47
#Sta/Elev= 30
  4586.4 1866.84  4626.4 1863.95  4653.7 1861.34  4658.7 1862.04  4676.8 1860.55
  4717.1 1854.35  4737.3 1852.97  4848.3 1853.49  4898.7 1852.77  4918.9 1851.82
  4957.8 1852.09  4969.3 1851.67  4997.0 1848.64  5009.0 1848.43  5009.5 1847.93
  5017.5 1847.93  5018.0 1848.43  5021.9 1848.67  5030.3 1850.51  5035.9 1848.93
  5044.3 1852.61  5052.7 1854.59  5058.3 1853.29  5066.6 1855.06  5089.0 1855.80
  5267.9 1857.49  5335.0 1858.69  5424.4 1859.58  5432.8 1859.25  5503.2 1860.79
#Mann=3,-1,0
  4586.4    0.05       0  5009.0    0.03       0  5018.0    0.05       0
Bank Sta=5009,5018
Exp/Cntr=0.3,0.1

Type RM Length L Ch R = 1,1428,289,289,289
BEGIN DESCRIPTION:
Deadman 36 2.0
END DESCRIPTION:
XS GIS Cut Line= 3
      1662905.00      6906487.99      1662955.00      6906688.00
      1663555.02      6907488.03
#Sta/Elev= 30
  4788.6 1871.02  4798.9 1870.40  4811.8 1868.21  4819.5 1865.39  4829.8 1863.10
  4840.1 1861.70  4930.3 1857.27  4953.5 1854.42  4963.8 1852.47  4971.6 1849.91
  4976.7 1847.40  4987.6 1846.90  4988.1 1846.40  4996.2 1846.40  4996.7 1846.90
  5031.2 1847.47  5058.3 1849.43  5102.1 1848.11  5144.8 1850.49  5202.1 1851.61
  5222.9 1851.47  5302.1 1854.28  5552.1 1856.93  5681.2 1859.12  5694.8 1859.91
  5716.6 1860.15  5722.9 1860.90  5752.1 1861.42  5916.6 1869.43  5994.8 1872.05
#Mann=3,-1,0
  4788.6    0.05       0  4987.6    0.05       0  4996.7    0.05       0
Bank Sta=4987.6,4996.7
Exp/Cntr=0.3,0.1

Type RM Length L Ch R = 1,1139,60,60,60
BEGIN DESCRIPTION:
Mapping XS b43b9202
END DESCRIPTION:
XS GIS Cut Line= 4
      1662781.91      6906518.85      1662786.50      6906858.31
      1662846.14      6907000.53      1663260.18      6907498.34
#Sta/Elev= 30
  4627.8 1869.69  4646.9 1867.84  4677.0 1861.61  4807.0 1854.26  4837.0 1847.20
  4867.0 1844.82  4937.0 1844.11  4974.4 1844.76  4979.8 1842.42  4998.1 1843.13
  4999.0 1842.06  4999.5 1841.56  5008.1 1842.06  5027.3 1843.98  5032.7 1842.63
  5051.1 1845.60  5056.5 1844.68  5074.9 1847.19  5080.3 1845.95  5104.1 1849.78
  5109.5 1848.01  5126.1 1850.16  5132.6 1849.01  5140.5 1849.62  5147.0 1848.60
  5196.4 1852.30  5452.9 1855.33  5601.3 1858.38  5687.3 1861.13  5769.0 1865.01
#Mann=3,-1,0
  4627.8    0.05       0  4999.0    0.05       0  5008.1    0.05       0
Bank Sta=4999,5008.1
Exp/Cntr=0.3,0.1

Type RM Length L Ch R = 1,1079,78,78,78
BEGIN DESCRIPTION:
Mapping XS 21b18acf
END DESCRIPTION:
XS GIS Cut Line= 4
      1662717.68      6906564.72      1662731.44      6906872.07
      1662772.73      6906963.83      1663095.92      6907492.96
#Sta/Elev= 30
  4674.4 1861.57  4787.8 1856.45  4847.9 1858.49  4927.9 1857.73  4937.9 1856.89
  4946.4 1854.50  4951.4 1857.77  4982.1 1856.93  4998.5 1855.58  5004.0 1858.36
  5010.5 1858.76  5027.1 1857.69  5043.4 1858.67  5050.3 1857.93  5100.9 1858.12
  5159.0 1857.15  5181.3 1857.60  5189.9 1856.21  5195.7 1853.37  5204.7 1852.10
  5235.3 1851.89  5235.8 1851.39  5243.9 1851.39  5244.4 1851.89  5333.6 1852.53
  5422.1 1854.03  5517.0 1856.51  5611.8 1857.68  5639.0 1858.82  5702.7 1859.98
#Mann=3,-1,0
  4674.4    0.05       0  5235.3    0.05       0  5244.4    0.05       0
Bank Sta=5235.3,5244.4
Exp/Cntr=0.3,0.1

Type RM Length L Ch R = 1,1001,328,328,328
BEGIN DESCRIPTION:
Mapping XS cfef4987
END DESCRIPTION:
XS GIS Cut Line= 4
      1662641.37      6906600.73      1662661.07      6906893.33
      1662708.90      6907081.84      1662855.17      6907363.14
#Sta/Elev= 30
  4711.7 1860.10  4729.0 1859.80  4769.1 1857.48  4819.2 1852.84  4829.2 1851.71
  4837.2 1849.88  4842.2 1850.73  4869.3 1847.95  4899.4 1846.82  4929.5 1846.77
  4944.9 1843.77  4945.4 1843.27  4953.6 1843.27  4954.1 1843.77  5009.9 1845.70
  5038.4 1848.09  5043.6 1847.78  5061.4 1848.43  5079.4 1850.05  5084.6 1848.71
  5102.6 1850.35  5112.9 1850.63  5194.9 1850.52  5223.4 1851.29  5245.5 1850.87
  5251.5 1851.69  5284.1 1851.12  5296.6 1850.43  5461.0 1853.09  5516.5 1854.65
#Mann=3,-1,0
  4711.7    0.05       0  4944.9    0.03       0  4954.1    0.05       0
Bank Sta=4944.9,4954.1
Exp/Cntr=0.3,0.1

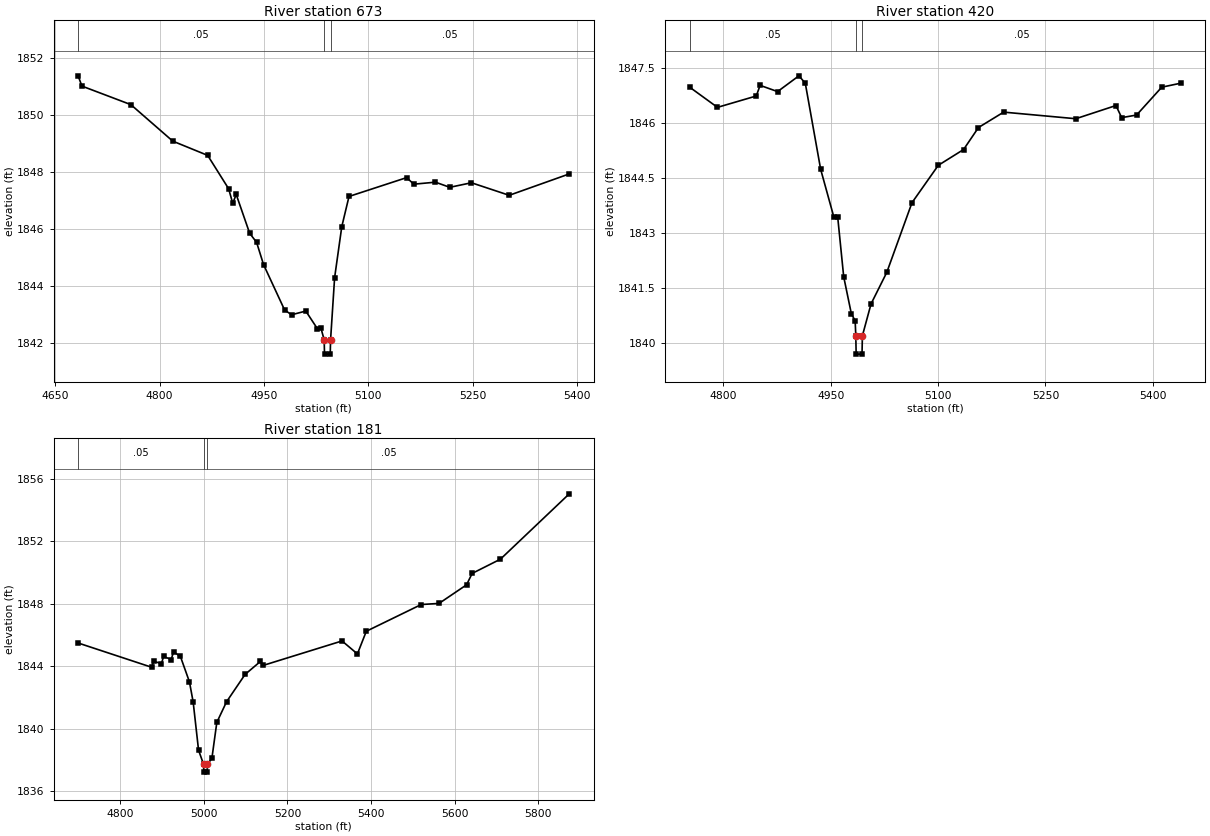
Type RM Length L Ch R = 1,673,253,253,253
BEGIN DESCRIPTION:
Mapping XS 57e0c8a2
END DESCRIPTION:
XS GIS Cut Line= 3
      1662360.01      6906572.53      1662331.87      6906884.89
      1662432.92      6907263.82
#Sta/Elev= 30
  4683.0 1851.37  4688.5 1851.01  4758.8 1850.36  4819.0 1849.08  4869.2 1848.58
  4899.3 1847.41  4905.2 1846.90  4910.2 1847.21  4929.5 1845.85  4939.5 1845.53
  4949.5 1844.75  4979.7 1843.16  4989.7 1842.99  5010.2 1843.12  5026.9 1842.50
  5032.1 1842.51  5036.6 1842.11  5037.1 1841.61  5045.3 1841.61  5045.8 1842.11
  5051.6 1844.29  5061.9 1846.08  5072.3 1847.14  5155.1 1847.80  5165.4 1847.57
  5196.5 1847.64  5217.1 1847.46  5248.2 1847.62  5302.5 1847.18  5388.8 1847.93
#Mann=3,-1,0
  4683.0    0.05       0  5036.6    0.03       0  5045.8    0.05       0
Bank Sta=5036.6,5045.8
Exp/Cntr=0.3,0.1

Type RM Length L Ch R = 1,420,239,239,239
BEGIN DESCRIPTION:
Mapping XS af223d4a
END DESCRIPTION:
XS GIS Cut Line= 3
      1662005.50      6906707.66      1662098.34      6906943.98
      1662368.46      6907281.63
#Sta/Elev= 30
  4753.0 1846.97  4791.8 1846.42  4846.0 1846.73  4851.4 1847.02  4875.8 1846.85
  4905.6 1847.28  4914.5 1847.08  4936.0 1844.73  4954.4 1843.43  4959.8 1843.43
  4968.2 1841.80  4978.9 1840.79  4984.2 1840.60  4985.1 1840.19  4985.6 1839.69
  4993.8 1839.69  4994.3 1840.19  5006.4 1841.06  5028.4 1841.92  5063.6 1843.82
  5100.4 1844.84  5135.7 1845.27  5156.5 1845.87  5191.7 1846.29  5292.5 1846.11
  5348.6 1846.47  5356.6 1846.14  5377.4 1846.21  5412.6 1846.97  5439.3 1847.08
#Mann=3,-1,0
  4753.0    0.05       0  4985.1    0.03       0  4994.3    0.05       0
Bank Sta=4985.1,4994.3
Exp/Cntr=0.3,0.1

Type RM Length L Ch R = 1,181,0,0,0
BEGIN DESCRIPTION:
Deadman 36 1.0
END DESCRIPTION:
XS GIS Cut Line= 3
      1661830.00      6906813.00      1661948.82      6907089.88
      1662694.76      6907546.50
#Sta/Elev= 30
  4698.7 1845.48  4874.5 1843.93  4879.9 1844.31  4898.1 1844.16  4903.5 1844.62
  4921.6 1844.42  4927.1 1844.91  4943.5 1844.63  4965.3 1842.99  4974.2 1841.70
  4987.1 1838.62  4999.1 1837.72  4999.6 1837.22  5007.8 1837.22  5008.3 1837.72
  5019.0 1838.10  5030.8 1840.40  5054.1 1841.72  5098.5 1843.47  5135.2 1844.30
  5141.1 1844.04  5330.6 1845.61  5367.4 1844.78  5388.7 1846.23  5520.2 1847.94
  5562.8 1848.01  5628.7 1849.20  5642.1 1849.93  5709.8 1850.84  5874.6 1855.02
#Mann=3,-1,0
  4698.7    0.05       0  4999.1    0.03       0  5008.3    0.05       0
Bank Sta=4999.1,5008.3
Exp/Cntr=0.3,0.1

Chan Stop Cuts=-1