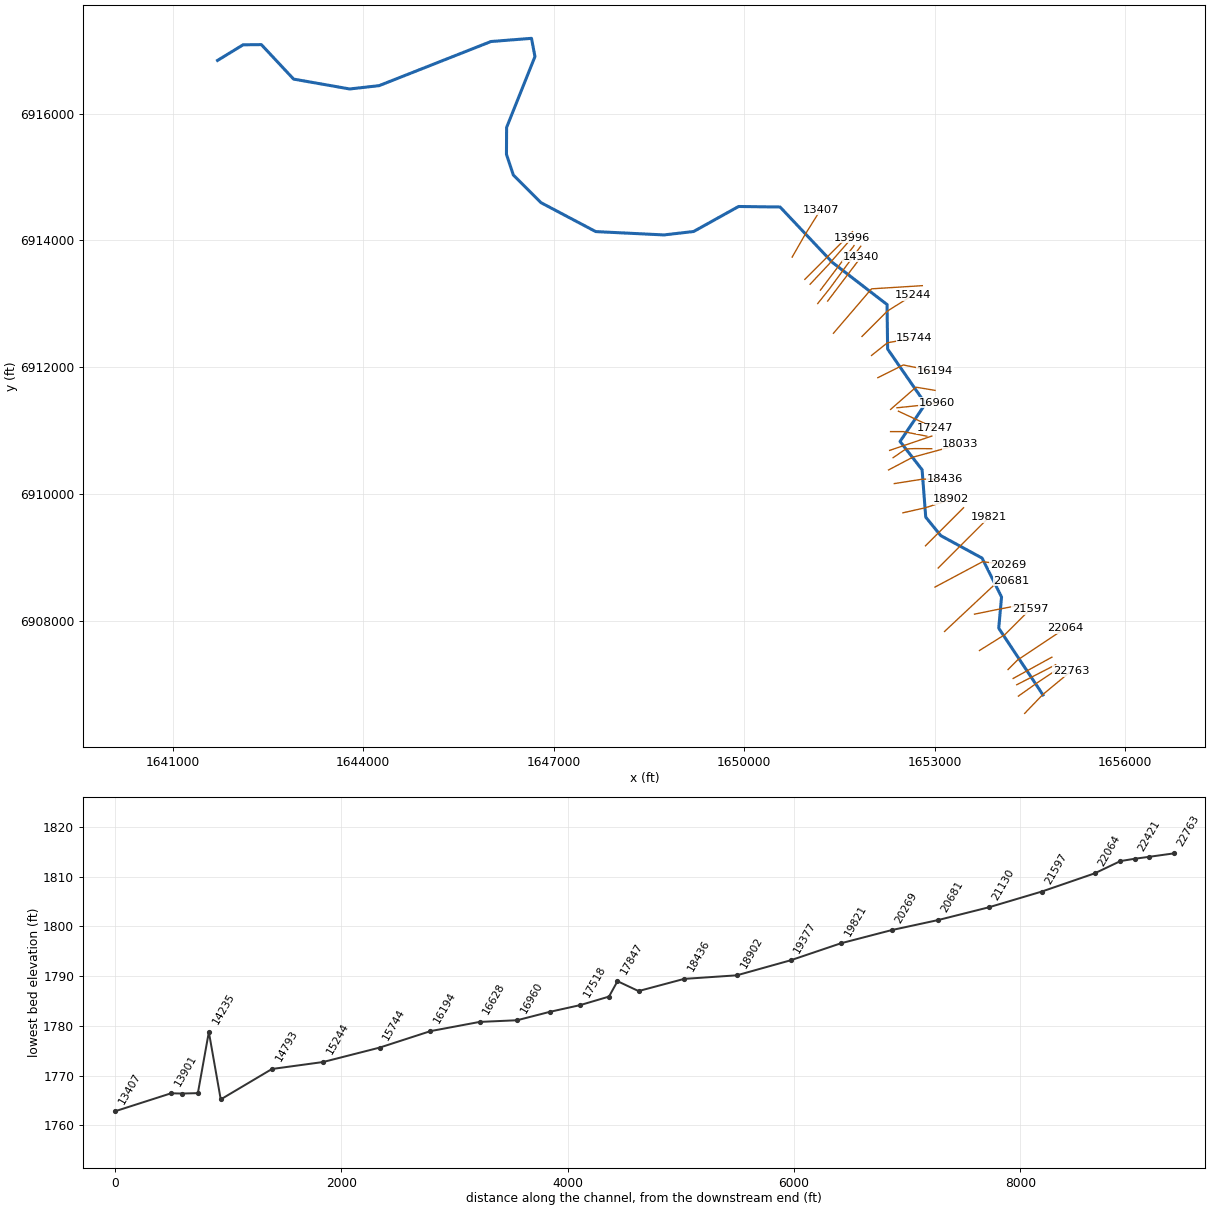
--- Deadman 37.prj (project) ---

Proj Title=Deadman 37 Base Level Engineering
Current Plan=p01
Default Exp/Contr=0.3,0.1
English Units
Geom File=g01
Flow File=f01
Plan File=p01
BEGIN DESCRIPTION:
Deadman 37
END DESCRIPTION:

--- Deadman 37.p01 (plan) ---

Plan Title=Multiple Run
Short Identifier=Multiple
Geom File=g01
Flow File=f01
Subcritical Flow
K Sum by GR= 0
Std Step Tol= 0.01
Critical Tol= 0.01
Num of Std Step Trials= 20
Max Error Tol= 0.3
Flow Tol Ratio= 0.001
Split Flow NTrial= 30
Split Flow Tol= 0.02
Split Flow Ratio= 0.02
Log Output Level= 0
Friction Slope Method= 1
Unsteady Friction Slope Method= 2
Unsteady Bridges Friction Slope Method= 1
Parabolic Critical Depth
Global Vel Dist=  1 , 1 , 1
Global Log Level= 0
CheckData=True
Encroach Param= -1, 0, 0, 0
BEGIN DESCRIPTION:
Multiple Run
END DESCRIPTION:

--- Deadman 37.f01 (steady flow) ---

Flow Title=Multiple
Number of Profiles=7
Profile Names=10-year,25-year,50-year,1pct_min,100-year,1pct_plu,500-year
River Rch & RM= Deadman 37,Reach-1,22763
     241     332     408     249     497     993     750
River Rch & RM= Deadman 37,Reach-1,22545
     352     494     613     379     756    1509    1164
River Rch & RM= Deadman 37,Reach-1,15244
     464     663     831     518    1034    2064    1624
River Rch & RM= Deadman 37,Reach-1,14793
     521     745     936     584    1164    2323    1829
River Rch & RM= Deadman 37,Reach-1,6535
     605     870    1097     687    1371    2736    2169
Boundary for River Rch & Prof#=Deadman 37,Reach-1,1
Up Type=0
Dn Type=3
Dn Slope=0.009
Boundary for River Rch & Prof#=Deadman 37,Reach-1,2
Up Type=0
Dn Type=3
Dn Slope=0.009
Boundary for River Rch & Prof#=Deadman 37,Reach-1,3
Up Type=0
Dn Type=3
Dn Slope=0.009
Boundary for River Rch & Prof#=Deadman 37,Reach-1,4
Up Type=0
Dn Type=3
Dn Slope=0.009
Boundary for River Rch & Prof#=Deadman 37,Reach-1,5
Up Type=0
Dn Type=3
Dn Slope=0.009
Boundary for River Rch & Prof#=Deadman 37,Reach-1,6
Up Type=0
Dn Type=3
Dn Slope=0.009
Boundary for River Rch & Prof#=Deadman 37,Reach-1,7
Up Type=0
Dn Type=3
Dn Slope=0.009

--- Deadman 37.g01 (geometry) ---

Geom Title=Existing Conditions

River Reach=Deadman 37,Reach-1
Reach XY= 30
      1654705.00      6906838.00      1654008.53      6907889.47
      1654052.83      6908382.03      1653746.86      6908994.06
      1653095.32      6909348.76      1652858.76      6909639.56
      1652801.45      6910386.53      1652454.19      6910832.97
      1652854.28      6911427.29      1652258.54      6912289.46
      1652249.54      6912990.45      1651388.33      6913654.65
      1650564.79      6914527.48      1649910.86      6914535.93
      1649203.44      6914141.76      1648734.85      6914087.64
      1647660.94      6914140.26      1646798.94      6914596.14
      1646363.14      6915031.94      1646255.07      6915358.03
      1646257.26      6915782.06      1646703.78      6916898.50
      1646649.35      6917186.03      1646010.94      6917135.73
      1644249.10      6916440.23      1643784.97      6916388.07
      1642902.56      6916543.52      1642394.56      6917086.94
      1642106.55      6917084.25      1641705.00      6916838.00

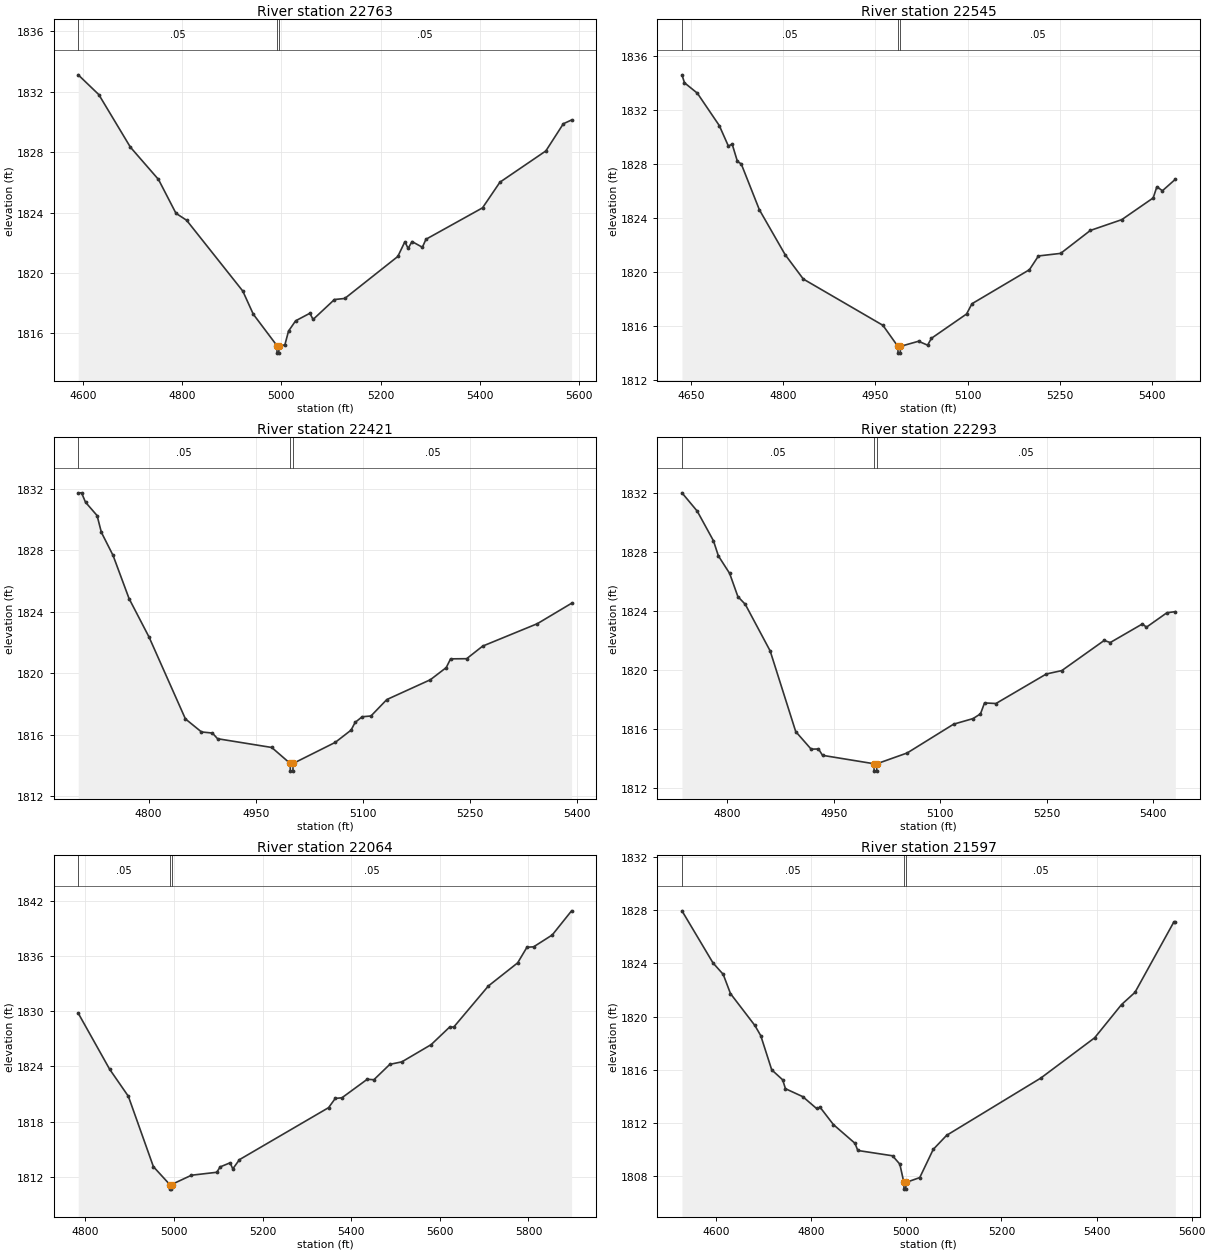
Type RM Length L Ch R = 1,22763,218,218,218
BEGIN DESCRIPTION:
Deadman 37 49.0
END DESCRIPTION:
XS GIS Cut Line= 3
      1654417.28      6906547.16      1654702.47      6906843.52
      1655150.72      6907215.36
#Sta/Elev= 30
  4590.9 1833.12  4632.4 1831.81  4696.0 1828.33  4752.6 1826.19  4787.8 1823.95
  4809.2 1823.49  4922.4 1818.80  4943.5 1817.27  4991.1 1815.19  4991.4 1814.69
  4994.9 1814.69  4995.1 1815.19  5007.1 1815.23  5014.5 1816.15  5028.8 1816.83
  5057.5 1817.33  5064.0 1816.92  5107.0 1818.24  5127.8 1818.31  5234.6 1821.09
  5248.9 1822.07  5255.4 1821.62  5263.2 1822.08  5284.1 1821.70  5291.3 1822.23
  5405.2 1824.31  5440.3 1826.01  5532.8 1828.08  5568.0 1829.88  5584.6 1830.13
#Mann=3,-1,0
  4590.9    0.05       0  4991.1    0.03       0  4995.1    0.05       0
Bank Sta=4991.1,4995.1
Exp/Cntr=0.3,0.1

Type RM Length L Ch R = 1,22545,124,124,124
BEGIN DESCRIPTION:
Mapping XS c9d9474b
END DESCRIPTION:
XS GIS Cut Line= 3
      1654318.50      6906819.28      1654607.41      6907024.32
      1654980.20      6907272.84
#Sta/Elev= 30
  4635.3 1834.62  4639.4 1834.03  4660.3 1833.26  4696.0 1830.86  4710.8 1829.34
  4716.9 1829.49  4725.5 1828.20  4731.7 1828.02  4761.2 1824.62  4803.0 1821.30
  4832.6 1819.49  4962.1 1816.06  4986.4 1814.50  4986.7 1814.00  4990.2 1814.00
  4990.5 1814.50  5020.0 1814.88  5034.7 1814.59  5041.0 1815.10  5098.1 1816.90
  5106.9 1817.66  5200.3 1820.18  5215.0 1821.20  5251.1 1821.39  5299.4 1823.09
  5350.5 1823.89  5401.6 1825.50  5407.6 1826.33  5416.6 1826.03  5437.6 1826.88
#Mann=3,-1,0
  4635.3    0.05       0  4986.4    0.03       0  4990.5    0.05       0
Bank Sta=4986.4,4990.5
Exp/Cntr=0.3,0.1

Type RM Length L Ch R = 1,22421,128,128,128
BEGIN DESCRIPTION:
Mapping XS e7735f69
END DESCRIPTION:
XS GIS Cut Line= 2
      1654291.55      6906998.01      1654905.62      6907313.34
#Sta/Elev= 30
  4701.6 1831.74  4706.3 1831.74  4711.8 1831.13  4728.0 1830.26  4734.0 1829.17
  4750.4 1827.66  4772.8 1824.85  4800.6 1822.36  4851.6 1817.02  4874.1 1816.17
  4889.3 1816.10  4896.6 1815.73  4972.4 1815.16  4998.2 1814.12  4998.4 1813.62
  5002.0 1813.62  5002.3 1814.12  5061.2 1815.49  5083.4 1816.29  5089.0 1816.79
  5098.9 1817.16  5111.2 1817.21  5133.4 1818.28  5194.3 1819.57  5216.5 1820.36
  5222.6 1820.93  5245.1 1820.94  5267.5 1821.76  5344.0 1823.22  5391.9 1824.55
#Mann=3,-1,0
  4701.6    0.05       0  4998.2    0.03       0  5002.3    0.05       0
Bank Sta=4998.2,5002.3
Exp/Cntr=0.3,0.1

Type RM Length L Ch R = 1,22293,229,229,229
BEGIN DESCRIPTION:
Mapping XS 9905b230
END DESCRIPTION:
XS GIS Cut Line= 2
      1654236.13      6907097.68      1654845.36      6907432.75
#Sta/Elev= 30
  4736.1 1832.00  4757.6 1830.76  4780.5 1828.75  4787.4 1827.73  4803.3 1826.54
  4814.9 1824.97  4825.3 1824.45  4860.4 1821.29  4896.4 1815.83  4918.1 1814.64
  4928.5 1814.65  4934.2 1814.22  5006.7 1813.65  5006.9 1813.15  5010.5 1813.15
  5010.8 1813.65  5053.5 1814.38  5118.9 1816.33  5146.4 1816.71  5156.8 1817.03
  5162.5 1817.77  5178.6 1817.73  5249.6 1819.73  5271.4 1819.96  5331.1 1822.00
  5339.7 1821.86  5385.0 1823.12  5390.7 1822.90  5419.6 1823.88  5431.4 1823.95
#Mann=3,-1,0
  4736.1    0.05       0  5006.7    0.03       0  5010.8    0.05       0
Bank Sta=5006.7,5010.8
Exp/Cntr=0.3,0.1

Type RM Length L Ch R = 1,22064,467,467,467
BEGIN DESCRIPTION:
Deadman 37 48.0
END DESCRIPTION:
XS GIS Cut Line= 3
      1654154.97      6907237.97      1654305.00      6907388.00
      1655055.03      6907888.02
#Sta/Elev= 30
  4783.7 1829.78  4854.5 1823.70  4896.9 1820.75  4953.4 1813.11  4990.3 1811.17
  4990.5 1810.67  4994.1 1810.67  4994.4 1811.17  5039.4 1812.18  5096.5 1812.50
  5104.0 1813.08  5126.6 1813.53  5132.6 1812.87  5147.6 1813.87  5348.9 1819.52
  5363.9 1820.52  5379.0 1820.59  5436.1 1822.60  5451.1 1822.55  5487.1 1824.22
  5514.2 1824.49  5580.3 1826.36  5622.3 1828.28  5631.4 1828.27  5709.5 1832.73
  5775.6 1835.24  5796.6 1836.94  5811.6 1836.98  5853.7 1838.27  5897.3 1840.89
#Mann=3,-1,0
  4783.7    0.05       0  4990.3    0.03       0  4994.4    0.05       0
Bank Sta=4990.3,4994.4
Exp/Cntr=0.3,0.1

Type RM Length L Ch R = 1,21597,467,467,467
BEGIN DESCRIPTION:
Deadman 37 47.0
END DESCRIPTION:
XS GIS Cut Line= 3
      1653705.00      6907538.00      1654105.00      6907788.00
      1654505.01      6908188.01
#Sta/Elev= 30
  4528.3 1827.96  4593.7 1824.03  4615.0 1823.18  4630.3 1821.73  4681.6 1819.33
  4694.0 1818.56  4717.0 1815.99  4740.0 1815.24  4745.9 1814.57  4782.4 1813.97
  4811.3 1813.08  4819.0 1813.16  4846.7 1811.87  4892.1 1810.46  4898.0 1809.92
  4971.1 1809.52  4986.4 1808.89  4994.9 1807.51  4995.2 1807.01  4998.8 1807.01
  4999.1 1807.51  5028.3 1807.88  5056.6 1810.00  5084.8 1811.06  5282.8 1815.37
  5396.0 1818.40  5452.5 1820.90  5480.8 1821.82  5562.1 1827.09  5565.7 1827.09
#Mann=3,-1,0
  4528.3    0.05       0  4994.9    0.03       0  4999.1    0.05       0
Bank Sta=4994.9,4999.1
Exp/Cntr=0.3,0.1

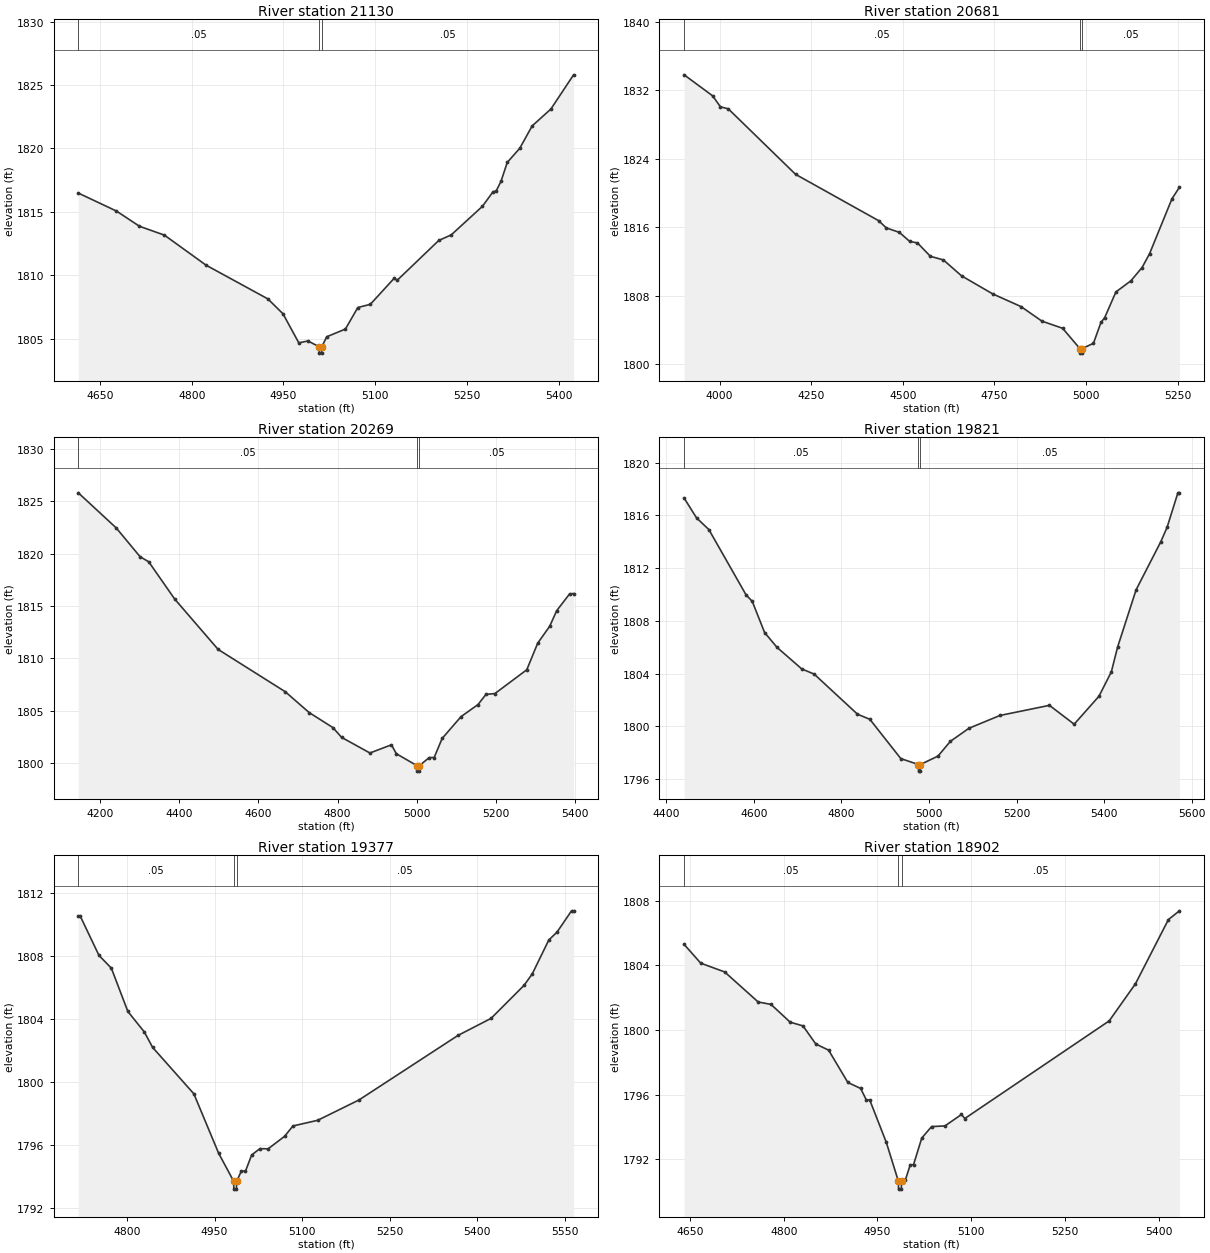
Type RM Length L Ch R = 1,21130,449,449,449
BEGIN DESCRIPTION:
Deadman 37 46.0
END DESCRIPTION:
XS GIS Cut Line= 3
      1653627.02      6908110.92      1654005.00      6908188.00
      1654421.48      6908267.22
#Sta/Elev= 30
  4614.6 1816.48  4677.0 1815.06  4714.6 1813.86  4755.4 1813.16  4823.5 1810.79
  4924.5 1808.13  4949.3 1806.95  4975.1 1804.66  4990.1 1804.81  5008.4 1804.35
  5008.7 1803.85  5012.4 1803.85  5012.7 1804.35  5020.7 1805.14  5051.3 1805.75
  5071.6 1807.45  5092.0 1807.70  5130.9 1809.75  5136.0 1809.60  5203.9 1812.74
  5224.3 1813.18  5275.2 1815.43  5292.6 1816.58  5297.7 1816.64  5305.7 1817.41
  5315.9 1818.90  5336.3 1820.01  5356.6 1821.78  5387.2 1823.11  5424.3 1825.81
#Mann=3,-1,0
  4614.6    0.05       0  5008.4    0.03       0  5012.7    0.05       0
Bank Sta=5008.4,5012.7
Exp/Cntr=0.3,0.1

Type RM Length L Ch R = 1,20681,412,412,412
BEGIN DESCRIPTION:
Deadman 37 45.0
END DESCRIPTION:
XS GIS Cut Line= 3
      1653154.98      6907837.98      1653955.00      6908588.00
      1654205.03      6908638.01
#Sta/Elev= 30
  3903.2 1833.78  3981.1 1831.32  4002.1 1830.05  4023.6 1829.81  4207.3 1822.16
  4433.9 1816.75  4454.9 1815.90  4490.6 1815.38  4518.9 1814.32  4539.9 1814.15
  4575.1 1812.59  4610.8 1812.16  4660.1 1810.31  4745.1 1808.20  4822.8 1806.71
  4879.4 1805.02  4936.1 1804.18  4983.7 1801.78  4984.0 1801.28  4987.7 1801.28
  4988.0 1801.78  5020.2 1802.43  5040.6 1804.86  5050.8 1805.42  5081.4 1808.42
  5122.2 1809.72  5152.8 1811.27  5173.2 1812.88  5234.4 1819.30  5254.8 1820.65
#Mann=3,-1,0
  3903.2    0.05       0  4983.7    0.05       0  4988.0    0.05       0
Bank Sta=4983.7,4988
Exp/Cntr=0.3,0.1

Type RM Length L Ch R = 1,20269,448,448,448
BEGIN DESCRIPTION:
Deadman 37 44.0
END DESCRIPTION:
XS GIS Cut Line= 3
      1653004.98      6908537.99      1653755.00      6908938.00
      1654154.97      6908888.00
#Sta/Elev= 30
  4144.1 1825.80  4240.1 1822.45  4300.3 1819.71  4322.3 1819.22  4388.1 1815.66
  4497.9 1810.86  4667.9 1806.82  4728.1 1804.84  4788.4 1803.40  4810.3 1802.47
  4881.9 1800.98  4936.4 1801.76  4948.8 1800.91  5002.0 1799.75  5002.3 1799.25
  5006.1 1799.25  5006.4 1799.75  5031.9 1800.54  5044.5 1800.55  5064.7 1802.37
  5112.5 1804.45  5155.4 1805.60  5175.5 1806.57  5198.2 1806.65  5278.8 1808.92
  5306.5 1811.46  5336.8 1813.07  5354.4 1814.55  5387.2 1816.16  5397.2 1816.19
#Mann=3,-1,0
  4144.1    0.05       0  5002.0    0.03       0  5006.4    0.05       0
Bank Sta=5002,5006.4
Exp/Cntr=0.3,0.1

Type RM Length L Ch R = 1,19821,444,444,444
BEGIN DESCRIPTION:
Deadman 37 43.0
END DESCRIPTION:
XS GIS Cut Line= 3
      1653055.02      6908838.02      1653455.00      6909238.00
      1653854.97      6909637.97
#Sta/Elev= 30
  4440.8 1817.31  4469.1 1815.81  4497.3 1814.92  4582.2 1809.97  4596.3 1809.48
  4624.6 1807.11  4652.9 1805.99  4709.5 1804.35  4737.8 1803.96  4836.7 1800.92
  4865.0 1800.53  4935.7 1797.55  4976.0 1797.10  4976.3 1796.60  4980.1 1796.60
  4980.4 1797.10  5020.6 1797.74  5048.9 1798.86  5091.3 1799.85  5162.0 1800.82
  5275.2 1801.59  5331.7 1800.16  5388.3 1802.28  5416.6 1804.13  5430.7 1805.99
  5473.1 1810.35  5529.7 1814.01  5543.9 1815.09  5568.6 1817.71  5572.1 1817.71
#Mann=3,-1,0
  4440.8    0.05       0  4976.0    0.05       0  4980.4    0.05       0
Bank Sta=4976,4980.4
Exp/Cntr=0.3,0.1

Type RM Length L Ch R = 1,19377,475,475,475
BEGIN DESCRIPTION:
Deadman 37 42.0
END DESCRIPTION:
XS GIS Cut Line= 3
      1652855.00      6909188.00      1653055.00      6909388.00
      1653454.98      6909787.98
#Sta/Elev= 30
  4716.5 1810.50  4720.0 1810.50  4751.9 1808.02  4773.1 1807.21  4801.4 1804.46
  4829.6 1803.16  4843.8 1802.18  4914.5 1799.23  4956.9 1795.46  4982.7 1793.68
  4983.0 1793.18  4987.4 1793.18  4987.8 1793.68  4995.8 1794.32  5002.9 1794.32
  5013.5 1795.35  5027.6 1795.75  5041.8 1795.74  5070.1 1796.54  5084.2 1797.19
  5126.6 1797.55  5197.3 1798.84  5367.0 1802.94  5423.6 1804.02  5480.2 1806.12
  5494.3 1806.85  5522.6 1809.00  5536.7 1809.50  5561.5 1810.85  5565.0 1810.85
#Mann=3,-1,0
  4716.5    0.05       0  4982.7    0.03       0  4987.8    0.05       0
Bank Sta=4982.7,4987.8
Exp/Cntr=0.3,0.1

Type RM Length L Ch R = 1,18902,466,466,466
BEGIN DESCRIPTION:
Deadman 37 41.0
END DESCRIPTION:
XS GIS Cut Line= 3
      1652499.38      6909708.21      1652855.00      6909788.00
      1653261.75      6909921.96
#Sta/Elev= 30
  4640.6 1805.30  4667.2 1804.14  4705.4 1803.60  4759.1 1801.74  4779.6 1801.59
  4810.3 1800.49  4830.8 1800.26  4851.3 1799.14  4871.8 1798.76  4902.6 1796.76
  4923.1 1796.39  4932.4 1795.66  4937.5 1795.69  4964.1 1793.06  4983.4 1790.66
  4983.8 1790.16  4988.2 1790.16  4988.6 1790.66  4994.8 1790.74  5002.5 1791.67
  5007.7 1791.67  5020.9 1793.32  5036.6 1794.03  5058.0 1794.07  5084.5 1794.78
  5089.8 1794.53  5320.9 1800.57  5363.0 1802.87  5415.7 1806.84  5433.3 1807.38
#Mann=3,-1,0
  4640.6    0.05       0  4983.4    0.03       0  4988.6    0.05       0
Bank Sta=4983.4,4988.6
Exp/Cntr=0.3,0.1

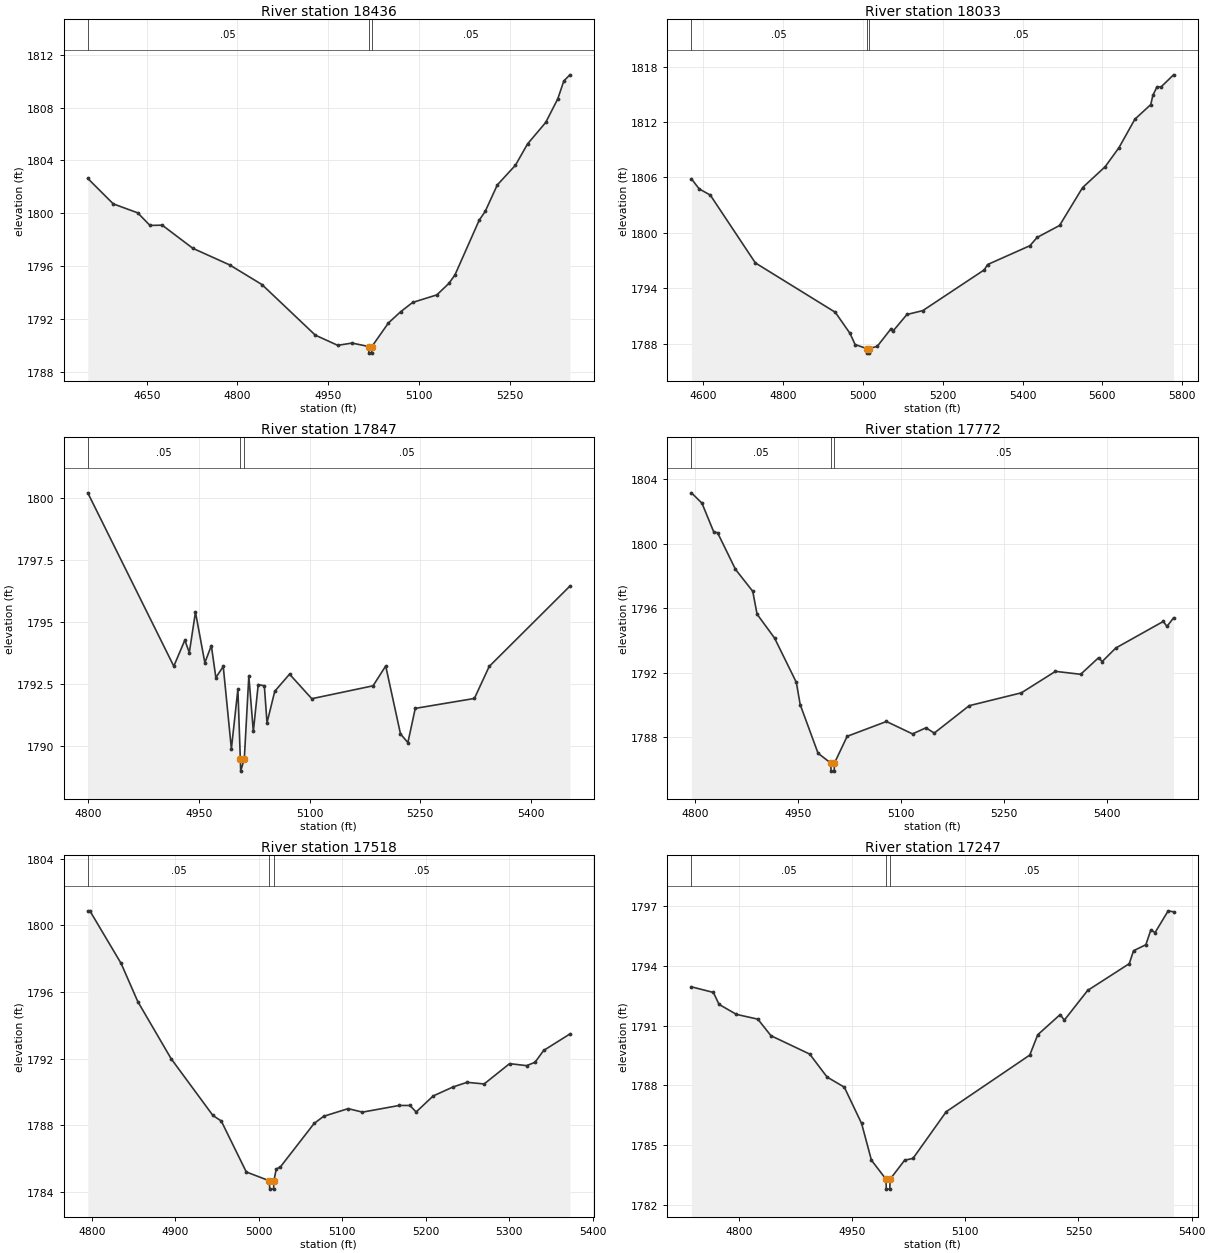
Type RM Length L Ch R = 1,18436,403,403,403
BEGIN DESCRIPTION:
Deadman 37 40.0
END DESCRIPTION:
XS GIS Cut Line= 3
      1652363.41      6910168.60      1652805.00      6910238.00
      1653154.99      6910238.00
#Sta/Elev= 30
  4552.6 1802.64  4594.7 1800.72  4635.2 1800.04  4655.4 1799.09  4675.7 1799.11
  4726.3 1797.36  4787.0 1796.11  4840.6 1794.62  4928.7 1790.80  4965.8 1790.03
  4989.5 1790.20  5017.0 1789.94  5017.4 1789.44  5021.9 1789.44  5022.3 1789.94
  5049.6 1791.72  5069.6 1792.56  5089.6 1793.27  5129.6 1793.84  5149.6 1794.71
  5159.6 1795.35  5199.6 1799.48  5209.6 1800.15  5229.6 1802.15  5259.6 1803.64
  5279.6 1805.25  5309.6 1806.87  5329.6 1808.66  5339.6 1810.01  5349.6 1810.47
#Mann=3,-1,0
  4552.6    0.05       0  5017.0    0.03       0  5022.3    0.05       0
Bank Sta=5017,5022.3
Exp/Cntr=0.3,0.1

Type RM Length L Ch R = 1,18033,186,186,186
BEGIN DESCRIPTION:
Deadman 37 39.0
END DESCRIPTION:
XS GIS Cut Line= 3
      1652273.18      6910383.81      1652653.57      6910584.11
      1653405.00      6910788.00
#Sta/Elev= 30
  4570.1 1805.85  4589.5 1804.76  4617.4 1804.09  4730.4 1796.75  4930.7 1791.41
  4967.7 1789.12  4980.4 1787.92  5009.1 1787.49  5009.6 1786.99  5014.1 1786.99
  5014.5 1787.49  5035.8 1787.72  5070.5 1789.63  5075.7 1789.39  5110.3 1791.17
  5150.1 1791.59  5304.2 1796.00  5312.3 1796.57  5418.5 1798.61  5436.7 1799.51
  5492.9 1800.80  5550.6 1804.90  5607.2 1807.16  5641.8 1809.22  5681.7 1812.30
  5721.5 1813.88  5726.8 1814.88  5737.2 1815.81  5747.5 1815.80  5778.6 1817.10
#Mann=3,-1,0
  4570.1    0.05       0  5009.1    0.03       0  5014.5    0.05       0
Bank Sta=5009.1,5014.5
Exp/Cntr=0.3,0.1

Type RM Length L Ch R = 1,17847,75,75,75
BEGIN DESCRIPTION:
Mapping XS f11b4641
END DESCRIPTION:
XS GIS Cut Line= 5
      1652344.71      6910576.75      1652491.97      6910677.41
      1652546.02      6910714.69      1652685.81      6910720.28
      1652954.17      6910718.42
#Sta/Elev= 30
  4800.0 1800.20  4916.4 1793.21  4931.3 1794.26  4937.4 1793.76  4945.7 1795.39
  4958.4 1793.35  4967.2 1794.04  4973.3 1792.75  4983.3 1793.20  4994.3 1789.88
  5003.1 1792.28  5006.4 1789.48  5006.9 1788.98  5011.8 1789.48  5017.9 1792.81
  5024.0 1790.58  5030.6 1792.47  5038.9 1792.42  5042.5 1790.93  5053.0 1792.20
  5073.0 1792.89  5103.1 1791.90  5186.0 1792.42  5203.1 1793.22  5223.1 1790.48
  5233.1 1790.13  5243.1 1791.51  5323.1 1791.91  5343.1 1793.20  5452.3 1796.44
#Mann=3,-1,0
  4800.0    0.05       0  5006.4    0.03       0  5011.8    0.05       0
Bank Sta=5006.4,5011.8
Exp/Cntr=0.3,0.1

Type RM Length L Ch R = 1,17772,254,254,254
BEGIN DESCRIPTION:
Mapping XS 775bcc88
END DESCRIPTION:
XS GIS Cut Line= 2
      1652290.55      6910691.97      1652954.55      6910917.64
#Sta/Elev= 30
  4795.2 1803.15  4810.5 1802.51  4827.9 1800.70  4833.2 1800.68  4859.3 1798.40
  4884.4 1797.04  4890.7 1795.62  4916.1 1794.14  4947.8 1791.39  4953.4 1790.01
  4979.4 1786.99  4997.9 1786.38  4998.3 1785.88  5002.8 1785.88  5003.3 1786.38
  5021.7 1788.04  5078.9 1788.96  5116.8 1788.19  5136.4 1788.57  5148.4 1788.24
  5199.2 1789.94  5275.2 1790.74  5324.7 1792.07  5361.4 1791.89  5387.5 1792.92
  5392.7 1792.68  5412.5 1793.52  5481.6 1795.17  5486.9 1794.86  5496.5 1795.39
#Mann=3,-1,0
  4795.2    0.05       0  4997.9    0.03       0  5003.3    0.05       0
Bank Sta=4997.9,5003.3
Exp/Cntr=0.3,0.1

Type RM Length L Ch R = 1,17518,271,271,271
BEGIN DESCRIPTION:
Deadman 37 38.0
END DESCRIPTION:
XS GIS Cut Line= 3
      1652304.96      6910988.00      1652505.00      6910988.00
      1652875.93      6910915.98
#Sta/Elev= 30
  4795.0 1800.87  4797.5 1800.87  4835.0 1797.71  4855.0 1795.42  4895.0 1791.99
  4945.0 1788.59  4955.0 1788.26  4985.0 1785.20  5012.7 1784.67  5013.1 1784.17
  5017.7 1784.17  5018.1 1784.67  5020.9 1785.37  5026.0 1785.51  5066.3 1788.11
  5077.7 1788.54  5107.1 1789.00  5124.3 1788.79  5168.2 1789.19  5181.1 1789.19
  5188.6 1788.80  5209.0 1789.76  5232.8 1790.30  5249.7 1790.58  5270.1 1790.48
  5300.6 1791.70  5321.0 1791.58  5331.1 1791.78  5341.4 1792.49  5372.9 1793.48
#Mann=3,-1,0
  4795.0    0.05       0  5012.7    0.05       0  5018.1    0.05       0
Bank Sta=5012.7,5018.1
Exp/Cntr=0.3,0.1

Type RM Length L Ch R = 1,17247,287,287,287
BEGIN DESCRIPTION:
Mapping XS 914ef9a8
END DESCRIPTION:
XS GIS Cut Line= 2
      1652428.61      6911309.25      1653008.28      6911040.84
#Sta/Elev= 30
  4737.2 1792.94  4766.3 1792.66  4773.8 1792.06  4796.8 1791.56  4825.2 1791.32
  4842.6 1790.49  4893.9 1789.57  4916.9 1788.42  4939.8 1787.91  4962.7 1786.09
  4975.7 1784.25  4995.0 1783.30  4995.4 1782.80  5000.0 1782.80  5000.5 1783.30
  5019.7 1784.25  5030.8 1784.34  5074.8 1786.68  5185.5 1789.52  5196.1 1790.54
  5225.8 1791.55  5231.3 1791.27  5262.2 1792.76  5317.3 1794.10  5323.0 1794.75
  5339.3 1795.05  5345.9 1795.79  5351.5 1795.66  5368.9 1796.75  5376.0 1796.70
#Mann=3,-1,0
  4737.2    0.05       0  4995.0    0.05       0  5000.5    0.05       0
Bank Sta=4995,5000.5
Exp/Cntr=0.3,0.1

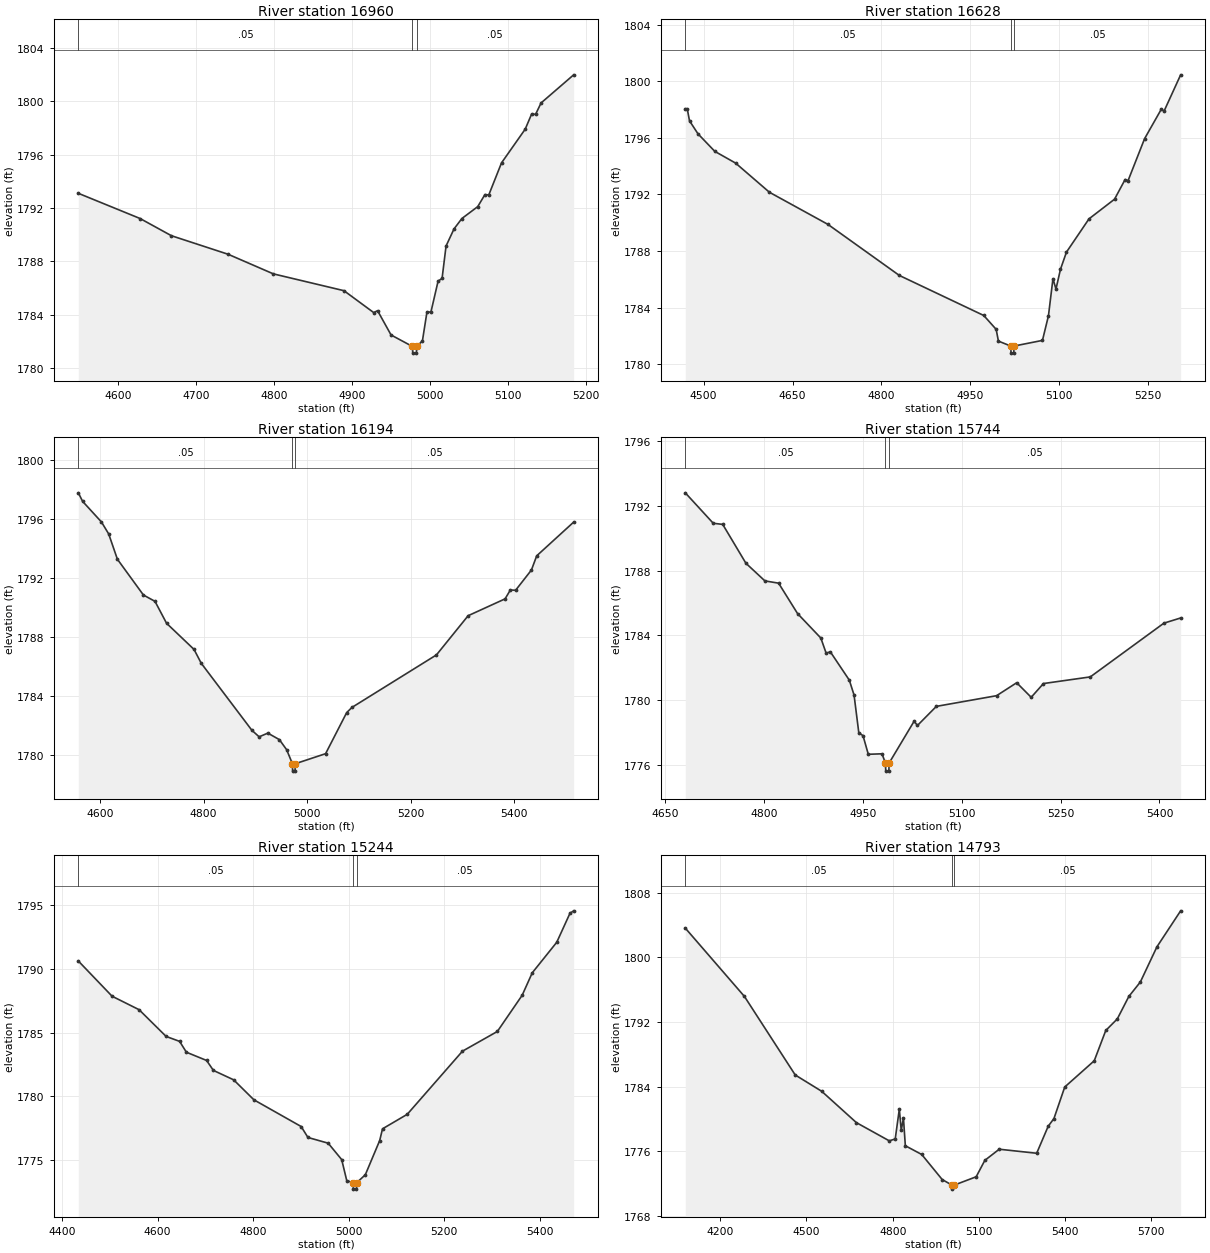
Type RM Length L Ch R = 1,16960,332,332,332
BEGIN DESCRIPTION:
Deadman 37 37.0
END DESCRIPTION:
XS GIS Cut Line= 3
      1652406.22      6911363.30      1652851.69      6911409.90
      1653036.19      6911441.58
#Sta/Elev= 30
  4549.4 1793.10  4628.6 1791.21  4668.8 1789.92  4741.5 1788.53  4799.5 1787.06
  4890.0 1785.80  4928.1 1784.16  4933.1 1784.30  4950.4 1782.48  4977.8 1781.62
  4978.2 1781.12  4982.8 1781.12  4983.3 1781.62  4990.6 1782.04  4996.4 1784.20
  5001.5 1784.20  5010.7 1786.52  5015.8 1786.72  5020.9 1789.15  5031.1 1790.43
  5041.2 1791.21  5061.5 1792.10  5070.7 1793.00  5075.7 1792.98  5092.0 1795.38
  5122.4 1797.91  5130.6 1799.04  5135.7 1799.02  5142.7 1799.87  5184.5 1801.98
#Mann=3,-1,0
  4549.4    0.05       0  4977.8    0.05       0  4983.3    0.05       0
Bank Sta=4977.8,4983.3
Exp/Cntr=0.3,0.1

Type RM Length L Ch R = 1,16628,434,434,434
BEGIN DESCRIPTION:
Deadman 37 36.0
END DESCRIPTION:
XS GIS Cut Line= 3
      1652305.00      6911338.00      1652705.00      6911688.00
      1653004.95      6911638.01
#Sta/Elev= 30
  4469.1 1798.05  4472.4 1798.05  4476.2 1797.20  4490.5 1796.28  4518.9 1795.04
  4554.0 1794.21  4611.0 1792.15  4709.7 1789.88  4830.2 1786.27  4972.6 1783.44
  4993.5 1782.46  4997.3 1781.63  5018.1 1781.28  5018.6 1780.78  5023.2 1780.78
  5023.6 1781.28  5071.6 1781.68  5081.7 1783.42  5089.3 1786.04  5094.4 1785.31
  5102.0 1786.71  5112.1 1787.92  5150.1 1790.27  5193.2 1791.66  5211.0 1793.05
  5216.0 1792.97  5243.9 1795.94  5271.8 1798.00  5276.9 1797.90  5304.7 1800.45
#Mann=3,-1,0
  4469.1    0.05       0  5018.1    0.05       0  5023.6    0.05       0
Bank Sta=5018.1,5023.6
Exp/Cntr=0.3,0.1

Type RM Length L Ch R = 1,16194,450,450,450
BEGIN DESCRIPTION:
Deadman 37 35.0
END DESCRIPTION:
XS GIS Cut Line= 3
      1652104.99      6911838.00      1652505.00      6912038.00
      1653004.97      6911938.01
#Sta/Elev= 30
  4558.0 1797.75  4566.4 1797.17  4602.7 1795.78  4616.7 1794.97  4633.5 1793.26
  4683.8 1790.84  4706.2 1790.41  4728.5 1788.93  4781.6 1787.16  4795.6 1786.22
  4893.4 1781.69  4907.4 1781.25  4924.2 1781.50  4946.5 1781.06  4960.5 1780.38
  4971.7 1779.43  4972.1 1778.93  4976.8 1778.93  4977.2 1779.43  5035.8 1780.11
  5076.6 1782.89  5086.8 1783.24  5250.0 1786.79  5311.2 1789.44  5382.6 1790.58
  5392.8 1791.18  5402.9 1791.16  5433.5 1792.53  5443.7 1793.49  5515.1 1795.77
#Mann=3,-1,0
  4558.0    0.05       0  4971.7    0.05       0  4977.2    0.05       0
Bank Sta=4971.7,4977.2
Exp/Cntr=0.3,0.1

Type RM Length L Ch R = 1,15744,500,500,500
BEGIN DESCRIPTION:
Deadman 37 34.0
END DESCRIPTION:
XS GIS Cut Line= 3
      1652005.04      6912188.03      1652255.00      6912388.00
      1652680.02      6912463.00
#Sta/Elev= 30
  4680.4 1792.80  4722.8 1790.92  4737.2 1790.85  4772.4 1788.45  4801.2 1787.36
  4822.0 1787.22  4850.8 1785.34  4886.1 1783.83  4894.1 1782.90  4900.5 1782.98
  4929.3 1781.23  4936.5 1780.31  4943.7 1777.98  4950.1 1777.80  4958.1 1776.65
  4978.9 1776.68  4984.1 1776.11  4984.6 1775.61  4989.3 1775.61  4989.7 1776.11
  5027.6 1778.69  5032.7 1778.43  5061.4 1779.61  5152.8 1780.27  5183.3 1781.07
  5205.3 1780.17  5223.9 1781.02  5295.0 1781.43  5406.7 1784.75  5432.1 1785.07
#Mann=3,-1,0
  4680.4    0.05       0  4984.1    0.05       0  4989.7    0.05       0
Bank Sta=4984.1,4989.7
Exp/Cntr=0.3,0.1

Type RM Length L Ch R = 1,15244,451,451,451
BEGIN DESCRIPTION:
Deadman 37 33.0
END DESCRIPTION:
XS GIS Cut Line= 3
      1651854.98      6912487.98      1652255.00      6912888.00
      1652654.99      6913138.00
#Sta/Elev= 30
  4433.9 1790.64  4504.6 1787.87  4561.2 1786.81  4617.8 1784.71  4646.1 1784.32
  4660.2 1783.47  4702.6 1782.82  4716.8 1782.04  4759.2 1781.30  4801.6 1779.73
  4900.6 1777.63  4914.8 1776.77  4957.2 1776.32  4985.5 1775.03  4996.1 1773.38
  5009.5 1773.21  5010.0 1772.71  5016.4 1772.71  5016.9 1773.21  5035.0 1773.84
  5065.1 1776.53  5071.0 1777.45  5122.8 1778.59  5238.4 1783.55  5311.5 1785.10
  5363.4 1787.94  5384.6 1789.71  5435.9 1792.11  5463.6 1794.39  5471.3 1794.58
#Mann=3,-1,0
  4433.9    0.05       0  5009.5    0.05       0  5016.9    0.05       0
Bank Sta=5009.5,5016.9
Exp/Cntr=0.3,0.1

Type RM Length L Ch R = 1,14793,453,453,453
BEGIN DESCRIPTION:
Deadman 37 32.0
END DESCRIPTION:
XS GIS Cut Line= 3
      1651404.99      6912537.99      1652005.00      6913238.00
      1652804.97      6913288.00
#Sta/Elev= 30
  4078.4 1803.62  4284.2 1795.16  4460.9 1785.44  4553.1 1783.42  4673.8 1779.54
  4788.0 1777.29  4808.8 1777.52  4823.1 1781.21  4829.7 1778.58  4837.4 1780.11
  4844.0 1776.68  4901.0 1775.60  4972.4 1772.49  5006.4 1771.81  5006.9 1771.31
  5014.3 1771.81  5090.5 1772.84  5120.6 1774.87  5170.7 1776.25  5301.0 1775.75
  5341.0 1779.09  5361.1 1780.05  5398.6 1783.95  5501.3 1787.20  5541.4 1790.95
  5581.5 1792.38  5621.6 1795.16  5661.7 1796.95  5719.3 1801.30  5801.9 1805.76
#Mann=3,-1,0
  4078.4    0.05       0  5006.4    0.05       0  5014.3    0.05       0
Bank Sta=5006.4,5014.3
Exp/Cntr=0.3,0.1

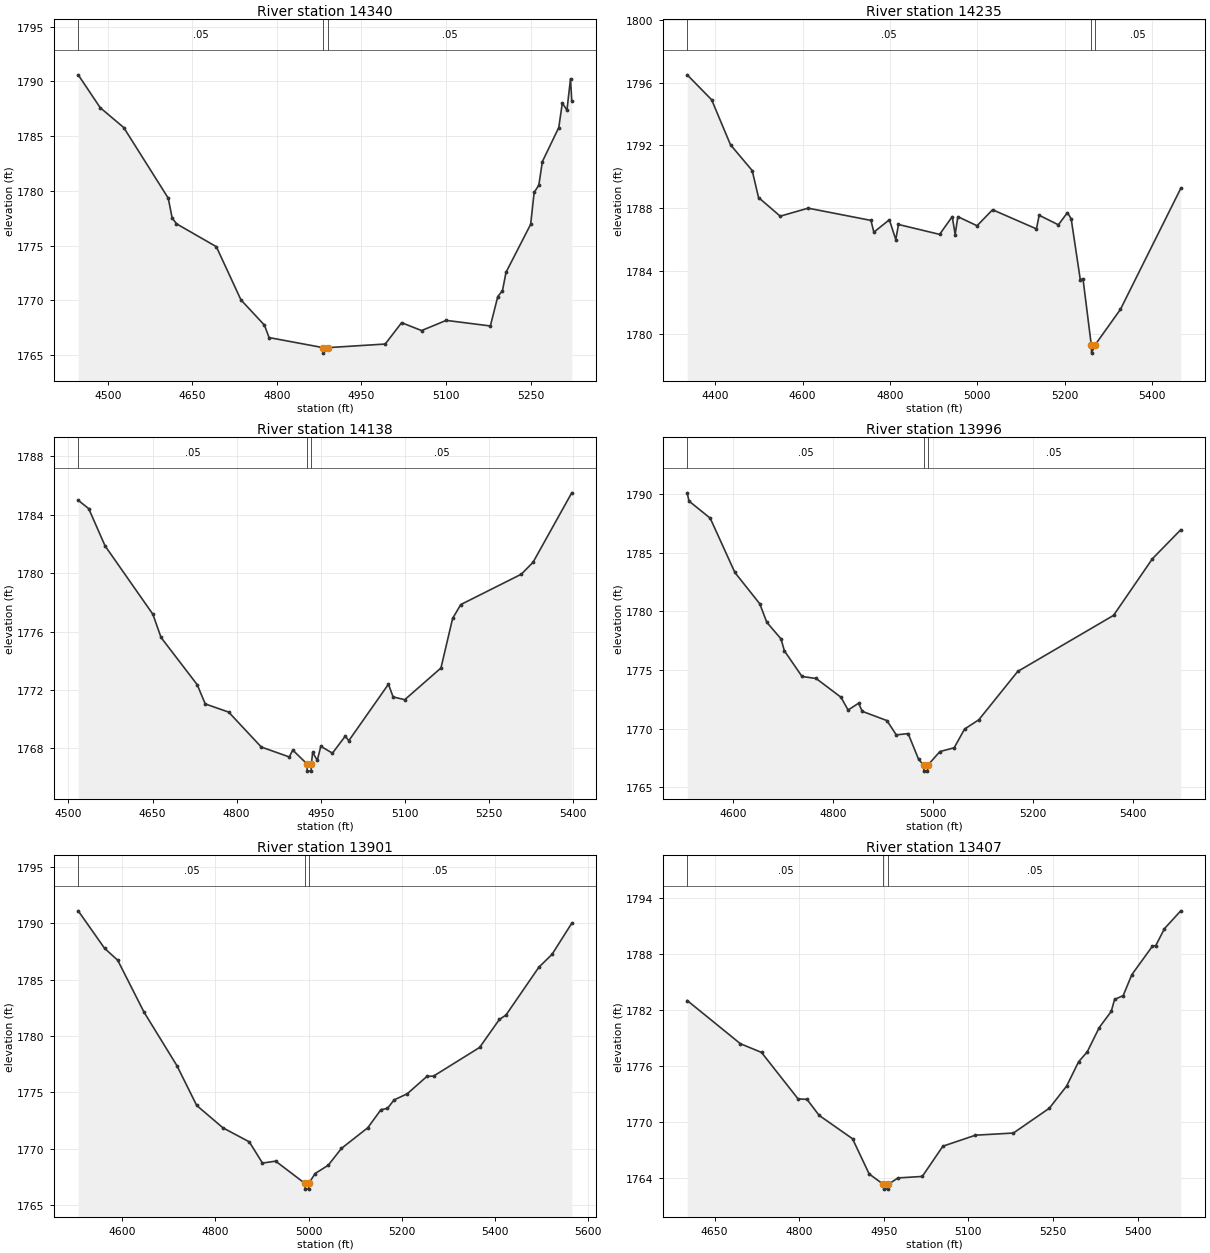
Type RM Length L Ch R = 1,14340,105,105,105
BEGIN DESCRIPTION:
Mapping XS a4f78b9f
END DESCRIPTION:
XS GIS Cut Line= 2
      1651313.93      6913045.22      1651842.55      6913743.11
#Sta/Elev= 30
  4447.5 1790.60  4486.5 1787.60  4528.2 1785.79  4607.2 1779.34  4614.1 1777.54
  4621.8 1777.00  4692.5 1774.91  4736.2 1770.05  4777.8 1767.75  4786.1 1766.61
  4882.0 1765.69  4882.5 1765.19  4889.9 1765.69  4992.1 1766.02  5021.2 1767.97
  5056.6 1767.25  5100.3 1768.18  5178.6 1767.67  5191.8 1770.36  5200.1 1770.89
  5206.4 1772.57  5250.1 1776.95  5256.3 1779.86  5264.6 1780.53  5270.9 1782.68
  5300.0 1785.79  5306.3 1788.03  5314.5 1787.37  5320.8 1790.25  5323.0 1788.25
#Mann=3,-1,0
  4447.5    0.05       0  4882.0    0.05       0  4889.9    0.05       0
Bank Sta=4882,4889.9
Exp/Cntr=0.3,0.1

Type RM Length L Ch R = 1,14235,97,97,97
BEGIN DESCRIPTION:
Mapping XS 819200e9
END DESCRIPTION:
XS GIS Cut Line= 3
      1651157.68      6913006.17      1651342.60      6913237.96
      1651834.79      6913909.85
#Sta/Elev= 30
  4336.0 1796.50  4391.9 1794.91  4435.1 1792.04  4484.7 1790.40  4499.2 1788.68
  4548.8 1787.49  4612.8 1788.00  4756.5 1787.22  4763.1 1786.47  4798.6 1787.26
  4813.3 1786.00  4819.5 1786.96  4913.6 1786.33  4942.5 1787.46  4949.2 1786.32
  4955.3 1787.46  4999.3 1786.88  5034.8 1787.90  5135.2 1786.68  5141.4 1787.55
  5185.4 1786.94  5206.2 1787.72  5214.7 1787.32  5235.5 1783.45  5241.7 1783.50
  5260.8 1779.26  5261.3 1778.76  5268.8 1779.26  5327.4 1781.55  5465.4 1789.26
#Mann=3,-1,0
  4336.0    0.05       0  5260.8    0.05       0  5268.8    0.05       0
Bank Sta=5260.8,5268.8
Exp/Cntr=0.3,0.1

Type RM Length L Ch R = 1,14138,142,142,142
BEGIN DESCRIPTION:
Mapping XS 12e891c9
END DESCRIPTION:
XS GIS Cut Line= 2
      1651199.38      6913217.15      1651730.30      6913919.83
#Sta/Elev= 30
  4517.4 1784.99  4536.1 1784.42  4565.3 1781.87  4650.6 1777.19  4665.2 1775.60
  4729.7 1772.37  4744.1 1771.05  4785.9 1770.49  4844.1 1768.10  4894.1 1767.42
  4900.3 1767.89  4925.5 1766.95  4926.0 1766.45  4933.0 1766.45  4933.5 1766.95
  4935.7 1767.73  4944.0 1767.19  4950.3 1768.15  4971.1 1767.68  4994.0 1768.85
  5000.2 1768.53  5071.0 1772.40  5079.3 1771.53  5100.1 1771.34  5164.7 1773.51
  5185.5 1776.90  5200.0 1777.85  5308.1 1779.93  5329.1 1780.75  5398.1 1785.50
#Mann=3,-1,0
  4517.4    0.05       0  4925.5    0.03       0  4933.5    0.05       0
Bank Sta=4925.5,4933.5
Exp/Cntr=0.3,0.1

Type RM Length L Ch R = 1,13996,95,95,95
BEGIN DESCRIPTION:
Mapping XS 0615c9c9
END DESCRIPTION:
XS GIS Cut Line= 3
      1651037.76      6913310.26      1651326.39      6913618.42
      1651698.36      6914044.46
#Sta/Elev= 30
  4508.2 1790.10  4511.7 1789.40  4554.2 1787.94  4603.6 1783.31  4653.4 1780.64
  4667.5 1779.06  4695.9 1777.65  4702.7 1776.63  4738.0 1774.44  4766.2 1774.27
  4816.0 1772.67  4830.2 1771.58  4851.2 1772.16  4858.5 1771.47  4907.9 1770.68
  4926.7 1769.46  4950.4 1769.57  4971.3 1767.38  4981.6 1766.87  4982.1 1766.37
  4989.1 1766.37  4989.6 1766.87  5014.0 1768.04  5042.5 1768.36  5063.4 1769.96
  5091.9 1770.75  5169.7 1774.87  5361.5 1779.65  5439.3 1784.48  5496.0 1786.95
#Mann=3,-1,0
  4508.2    0.05       0  4981.6    0.05       0  4989.6    0.05       0
Bank Sta=4981.6,4989.6
Exp/Cntr=0.3,0.1

Type RM Length L Ch R = 1,13901,494,494,494
BEGIN DESCRIPTION:
Deadman 37 30.0
END DESCRIPTION:
XS GIS Cut Line= 3
      1650954.98      6913387.98      1651305.00      6913738.00
      1651705.01      6914138.01
#Sta/Elev= 30
  4505.0 1791.09  4561.6 1787.77  4589.9 1786.71  4646.4 1782.11  4717.2 1777.36
  4759.6 1773.84  4816.2 1771.85  4872.7 1770.61  4901.0 1768.73  4929.3 1768.90
  4992.5 1766.92  4993.0 1766.42  5000.0 1766.42  5000.5 1766.92  5014.1 1767.80
  5042.4 1768.54  5070.7 1770.03  5127.3 1771.86  5155.6 1773.46  5169.7 1773.58
  5183.9 1774.33  5212.1 1774.87  5254.6 1776.42  5268.7 1776.44  5367.7 1778.98
  5410.1 1781.46  5424.3 1781.85  5495.0 1786.09  5523.3 1787.23  5565.7 1789.99
#Mann=3,-1,0
  4505.0    0.05       0  4992.5    0.03       0  5000.5    0.05       0
Bank Sta=4992.5,5000.5
Exp/Cntr=0.3,0.1

Type RM Length L Ch R = 1,13407,145,145,145
BEGIN DESCRIPTION:
Deadman 37 29.0
END DESCRIPTION:
XS GIS Cut Line= 3
      1650755.01      6913738.02      1650955.00      6914088.00
      1651205.01      6914488.01
#Sta/Elev= 30
  4601.6 1783.02  4695.9 1778.39  4733.3 1777.46  4798.1 1772.48  4813.9 1772.43
  4835.5 1770.71  4894.6 1768.21  4924.1 1764.44  4949.5 1763.31  4950.0 1762.81
  4957.2 1762.81  4957.7 1763.31  4975.2 1764.01  5018.3 1764.17  5054.8 1767.41
  5112.6 1768.59  5179.8 1768.82  5243.5 1771.48  5274.1 1773.85  5295.4 1776.46
  5310.7 1777.52  5331.9 1780.12  5353.2 1781.85  5359.1 1783.13  5374.4 1783.55
  5389.7 1785.79  5426.3 1788.85  5432.2 1788.91  5447.5 1790.72  5476.4 1792.63
#Mann=3,-1,0
  4601.6    0.05       0  4949.5    0.03       0  4957.7    0.05       0
Bank Sta=4949.5,4957.7
Exp/Cntr=0.3,0.1