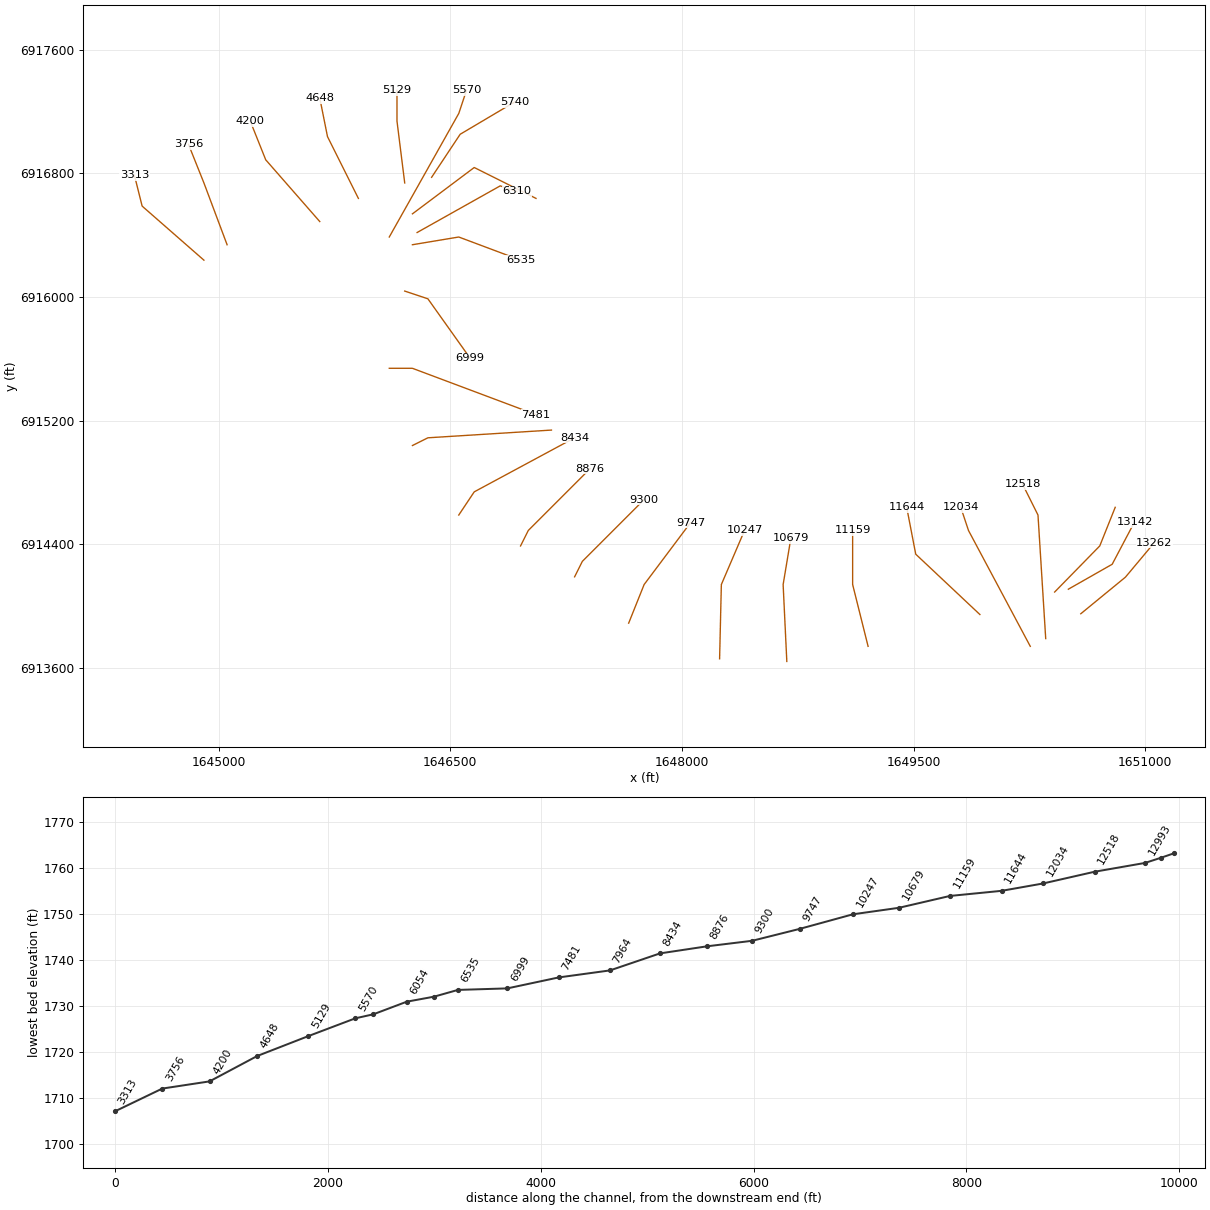
HEC-RAS study Deadman 37.prj: Deadman 37 Base Level Engineering

--- Deadman 37.g01 (geometry) --- (continued)

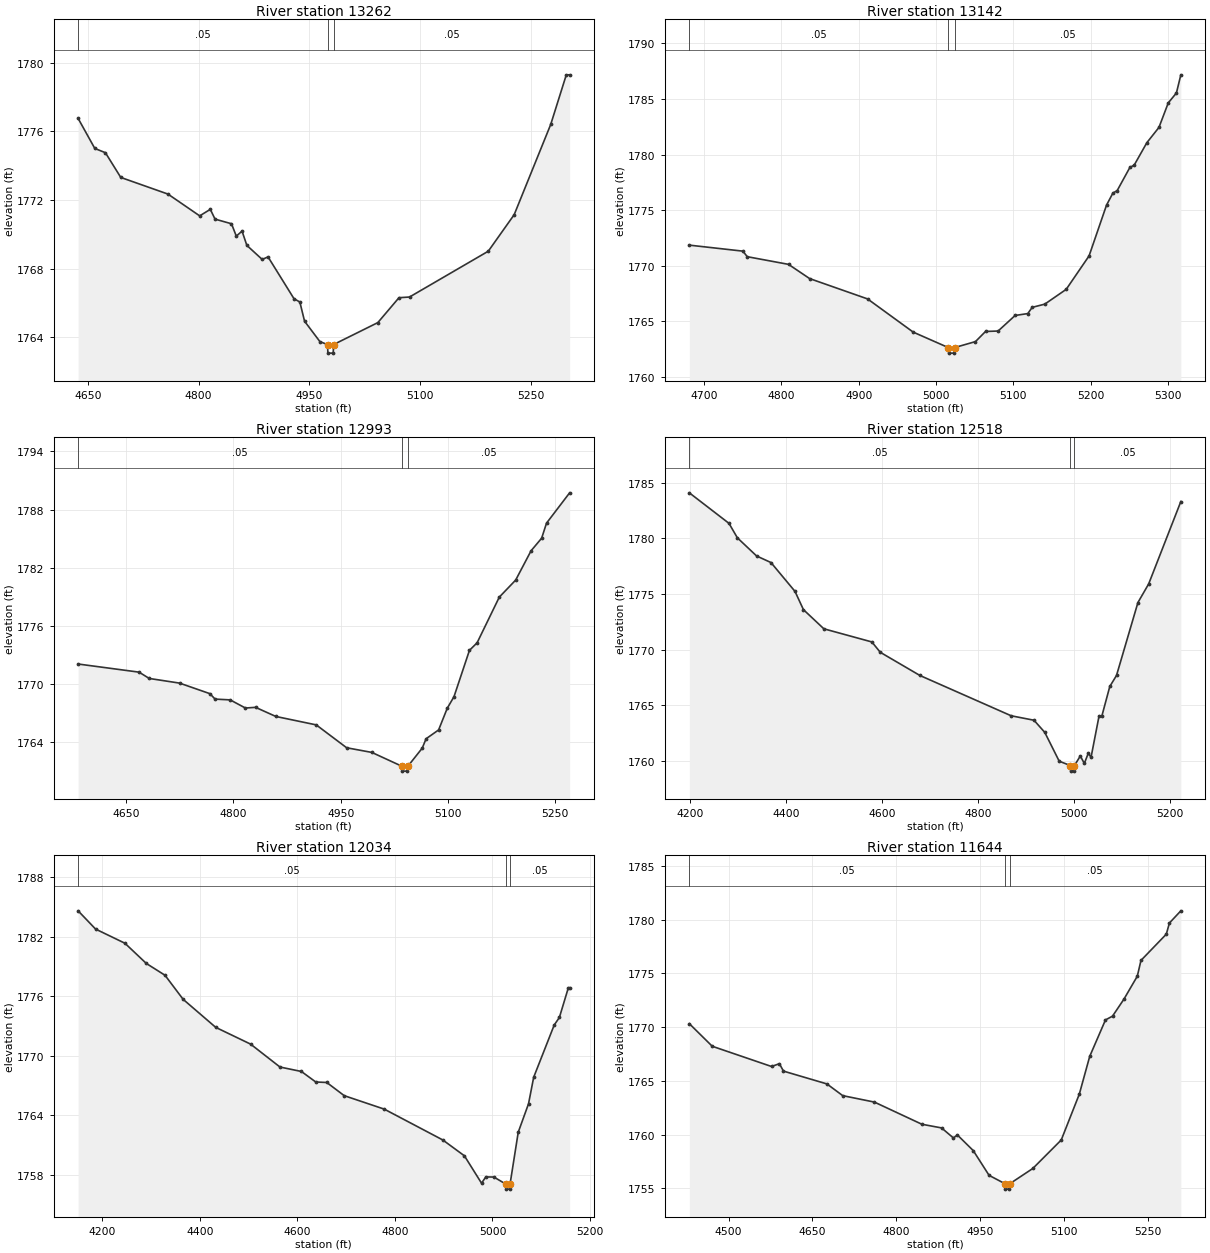
Type RM Length L Ch R = 1,13262,120,120,120
BEGIN DESCRIPTION:
Mapping XS 2e772a37
END DESCRIPTION:
XS GIS Cut Line= 3
      1650582.19      6913948.91      1650871.24      6914185.88
      1651058.77      6914409.87
#Sta/Elev= 30
  4636.7 1776.76  4659.3 1775.01  4673.7 1774.76  4694.5 1773.32  4758.4 1772.35
  4801.4 1771.08  4815.8 1771.46  4822.2 1770.89  4844.5 1770.62  4851.0 1769.90
  4858.8 1770.19  4865.3 1769.36  4886.1 1768.54  4894.0 1768.69  4929.2 1766.25
  4937.1 1766.06  4943.5 1764.94  4964.3 1763.75  4974.6 1763.58  4975.1 1763.08
  4982.3 1763.08  4982.8 1763.58  5042.8 1764.86  5071.4 1766.31  5085.7 1766.35
  5192.4 1769.02  5227.5 1771.15  5277.0 1776.41  5298.1 1779.30  5302.6 1779.30
#Mann=3,-1,0
  4636.7    0.05       0  4974.6    0.05       0  4982.8    0.05       0
Bank Sta=4974.6,4982.8
Exp/Cntr=0.3,0.1

Type RM Length L Ch R = 1,13142,149,149,149
BEGIN DESCRIPTION:
Mapping XS 766365bc
END DESCRIPTION:
XS GIS Cut Line= 3
      1650501.49      6914107.78      1650785.31      6914269.21
      1650929.97      6914543.03
#Sta/Elev= 30
  4680.7 1771.85  4750.0 1771.31  4755.7 1770.81  4809.1 1770.12  4836.4 1768.84
  4911.4 1767.01  4970.5 1764.02  5015.9 1762.63  5016.4 1762.13  5023.6 1762.13
  5024.1 1762.63  5051.1 1763.17  5064.1 1764.08  5080.4 1764.12  5102.4 1765.52
  5118.8 1765.69  5124.5 1766.25  5140.8 1766.54  5168.5 1767.87  5198.1 1770.88
  5220.7 1775.45  5228.9 1776.53  5234.5 1776.76  5250.9 1778.84  5256.5 1779.05
  5272.9 1781.07  5288.6 1782.45  5300.6 1784.65  5311.2 1785.55  5316.9 1787.18
#Mann=3,-1,0
  4680.7    0.05       0  5015.9    0.05       0  5024.1    0.05       0
Bank Sta=5015.9,5024.1
Exp/Cntr=0.3,0.1

Type RM Length L Ch R = 1,12993,475,475,475
BEGIN DESCRIPTION:
Deadman 37 28.0
END DESCRIPTION:
XS GIS Cut Line= 3
      1650412.91      6914089.52      1650705.00      6914388.00
      1650805.01      6914638.02
#Sta/Elev= 30
  4583.1 1772.06  4668.3 1771.22  4682.5 1770.57  4724.9 1770.09  4767.3 1769.00
  4774.5 1768.44  4795.6 1768.36  4816.9 1767.52  4831.1 1767.59  4859.4 1766.65
  4915.9 1765.78  4958.4 1763.42  4993.6 1762.94  5035.7 1761.51  5036.2 1761.01
  5043.4 1761.01  5043.9 1761.51  5064.0 1763.38  5069.4 1764.35  5086.9 1765.26
  5099.0 1767.50  5108.4 1768.69  5130.0 1773.47  5140.7 1774.25  5171.7 1778.96
  5194.6 1780.72  5216.1 1783.74  5230.9 1785.04  5237.7 1786.59  5270.0 1789.72
#Mann=3,-1,0
  4583.1    0.05       0  5035.7    0.05       0  5043.9    0.05       0
Bank Sta=5035.7,5043.9
Exp/Cntr=0.3,0.1

Type RM Length L Ch R = 1,12518,484,484,484
BEGIN DESCRIPTION:
Deadman 37 27.0
END DESCRIPTION:
XS GIS Cut Line= 3
      1650355.00      6913787.99      1650305.00      6914588.00
      1650204.99      6914788.02
#Sta/Elev= 30
  4198.3 1784.08  4281.0 1781.34  4298.5 1780.04  4338.6 1778.41  4368.6 1777.82
  4418.7 1775.23  4436.3 1773.59  4478.9 1771.87  4579.0 1770.69  4596.6 1769.76
  4679.2 1767.68  4869.6 1764.06  4917.2 1763.66  4939.7 1762.57  4969.8 1759.98
  4993.2 1759.59  4993.7 1759.09  5001.1 1759.09  5001.6 1759.59  5013.8 1760.45
  5022.2 1759.78  5030.6 1760.71  5036.2 1760.33  5053.0 1764.06  5058.6 1764.01
  5075.3 1766.69  5089.3 1767.68  5134.0 1774.23  5156.4 1775.90  5223.5 1783.30
#Mann=3,-1,0
  4198.3    0.05       0  4993.2    0.03       0  5001.6    0.05       0
Bank Sta=4993.2,5001.6
Exp/Cntr=0.3,0.1

Type RM Length L Ch R = 1,12034,390,390,390
BEGIN DESCRIPTION:
Deadman 37 26.0
END DESCRIPTION:
XS GIS Cut Line= 3
      1650255.01      6913737.97      1649855.00      6914488.00
      1649805.01      6914637.96
#Sta/Elev= 30
  4150.1 1784.62  4185.9 1782.78  4246.1 1781.35  4290.0 1779.31  4328.3 1778.12
  4365.5 1775.69  4432.4 1772.86  4503.9 1771.17  4564.1 1768.86  4608.1 1768.41
  4637.5 1767.35  4660.1 1767.30  4695.9 1765.97  4778.1 1764.61  4898.1 1761.50
  4942.4 1759.90  4977.5 1757.14  4986.3 1757.77  5002.8 1757.76  5027.6 1757.04
  5028.1 1756.54  5035.5 1756.54  5036.0 1757.04  5052.8 1762.28  5073.9 1765.15
  5084.5 1767.83  5126.6 1773.10  5137.2 1773.86  5155.6 1776.86  5158.2 1776.86
#Mann=3,-1,0
  4150.1    0.05       0  5027.6    0.03       0  5036.0    0.05       0
Bank Sta=5027.6,5036
Exp/Cntr=0.3,0.1

Type RM Length L Ch R = 1,11644,485,485,485
BEGIN DESCRIPTION:
Deadman 37 25.0
END DESCRIPTION:
XS GIS Cut Line= 3
      1649928.80      6913943.96      1649513.48      6914334.50
      1649455.00      6914638.02
#Sta/Elev= 30
  4429.9 1770.32  4470.9 1768.22  4576.9 1766.34  4591.0 1766.60  4598.3 1765.91
  4676.0 1764.72  4704.3 1763.63  4761.0 1763.03  4845.9 1760.97  4881.1 1760.63
  4902.2 1759.70  4909.5 1759.97  4937.8 1758.52  4966.1 1756.22  4994.7 1755.44
  4995.2 1754.94  5002.6 1754.94  5003.1 1755.44  5044.3 1756.86  5095.2 1759.51
  5127.5 1763.77  5146.1 1767.28  5174.3 1770.67  5186.9 1771.02  5207.2 1772.59
  5231.2 1774.73  5237.8 1776.20  5283.1 1778.64  5288.7 1779.68  5309.1 1780.81
#Mann=3,-1,0
  4429.9    0.05       0  4994.7    0.05       0  5003.1    0.05       0
Bank Sta=4994.7,5003.1
Exp/Cntr=0.3,0.1

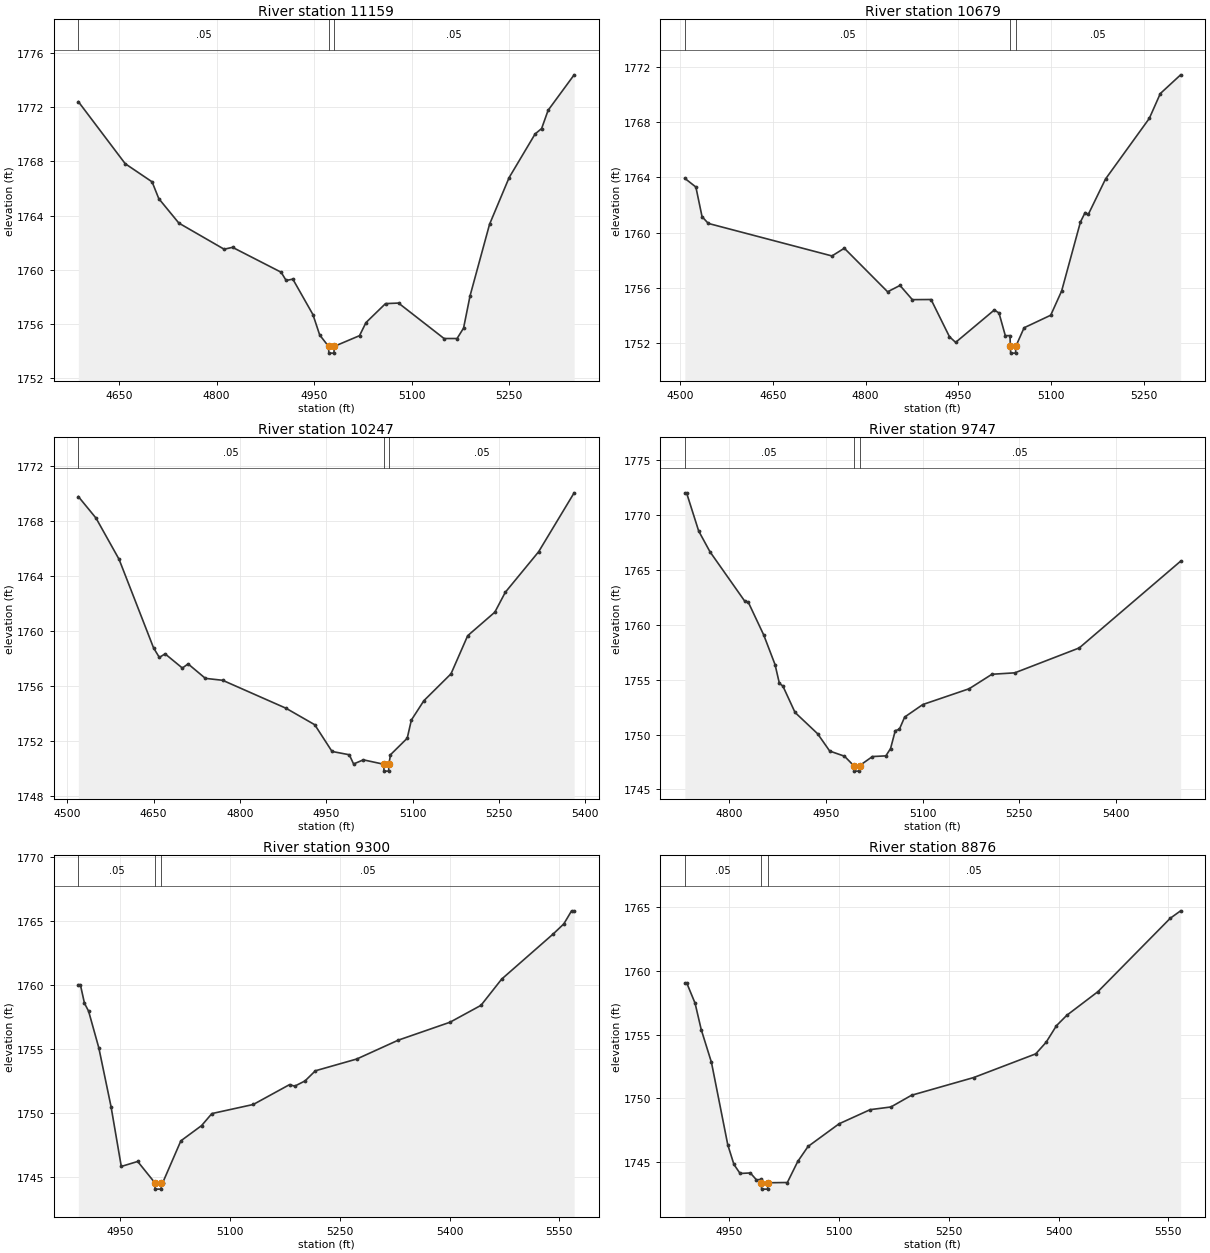
Type RM Length L Ch R = 1,11159,480,480,480
BEGIN DESCRIPTION:
Deadman 37 24.0
END DESCRIPTION:
XS GIS Cut Line= 3
      1649204.99      6913738.03      1649105.00      6914138.00
      1649105.00      6914488.02
#Sta/Elev= 30
  4587.5 1772.42  4659.6 1767.83  4700.9 1766.49  4711.2 1765.25  4742.1 1763.44
  4811.7 1761.51  4824.6 1761.65  4899.3 1759.81  4907.0 1759.20  4917.3 1759.30
  4948.2 1756.68  4958.6 1755.17  4972.2 1754.33  4972.7 1753.83  4980.5 1753.83
  4981.0 1754.33  5019.8 1755.12  5029.8 1756.09  5059.8 1757.49  5079.8 1757.53
  5149.8 1754.91  5169.8 1754.91  5179.8 1755.68  5189.8 1758.07  5219.8 1763.36
  5249.8 1766.80  5289.8 1770.03  5299.8 1770.43  5309.8 1771.78  5349.8 1774.40
#Mann=3,-1,0
  4587.5    0.05       0  4972.2    0.03       0  4981.0    0.05       0
Bank Sta=4972.2,4981
Exp/Cntr=0.3,0.1

Type RM Length L Ch R = 1,10679,432,432,432
BEGIN DESCRIPTION:
Deadman 37 23.0
END DESCRIPTION:
XS GIS Cut Line= 3
      1648678.82      6913640.09      1648655.00      6914138.00
      1648705.00      6914437.98
#Sta/Elev= 30
  4507.3 1763.93  4525.2 1763.30  4535.2 1761.15  4545.3 1760.66  4745.5 1758.30
  4765.5 1758.86  4835.6 1755.70  4855.6 1756.16  4875.6 1755.13  4905.9 1755.14
  4935.7 1752.44  4945.7 1752.03  5008.3 1754.38  5015.9 1754.16  5026.1 1752.52
  5033.7 1752.52  5034.3 1751.75  5034.8 1751.25  5042.7 1751.25  5043.2 1751.75
  5056.5 1753.09  5099.6 1754.00  5117.3 1755.76  5147.7 1760.76  5155.3 1761.45
  5160.4 1761.31  5188.3 1763.88  5259.2 1768.28  5277.0 1770.08  5309.9 1771.44
#Mann=3,-1,0
  4507.3    0.05       0  5034.3    0.03       0  5043.2    0.05       0
Bank Sta=5034.3,5043.2
Exp/Cntr=0.3,0.1

Type RM Length L Ch R = 1,10247,500,500,500
BEGIN DESCRIPTION:
Deadman 37 22.0
END DESCRIPTION:
XS GIS Cut Line= 3
      1648243.64      6913657.24      1648255.00      6914138.00
      1648405.01      6914488.02
#Sta/Elev= 30
  4519.1 1769.79  4549.9 1768.22  4589.9 1765.23  4649.9 1758.79  4659.9 1758.10
  4669.9 1758.36  4699.9 1757.33  4709.9 1757.63  4739.9 1756.58  4769.9 1756.44
  4880.0 1754.41  4930.0 1753.21  4960.0 1751.27  4990.0 1751.03  4997.5 1750.36
  5014.5 1750.66  5049.9 1750.34  5050.4 1749.84  5058.4 1749.84  5058.9 1750.34
  5061.6 1751.03  5090.7 1752.23  5097.9 1753.55  5119.7 1754.96  5166.8 1756.91
  5195.8 1759.68  5243.0 1761.39  5261.1 1762.83  5319.1 1765.78  5380.8 1770.06
#Mann=3,-1,0
  4519.1    0.05       0  5049.9    0.05       0  5058.9    0.05       0
Bank Sta=5049.9,5058.9
Exp/Cntr=0.3,0.1

Type RM Length L Ch R = 1,9747,447,447,447
BEGIN DESCRIPTION:
Deadman 37 21.0
END DESCRIPTION:
XS GIS Cut Line= 3
      1647655.01      6913888.02      1647755.00      6914138.00
      1648054.98      6914537.97
#Sta/Elev= 30
  4731.2 1772.04  4733.9 1772.04  4752.7 1768.56  4770.2 1766.67  4824.1 1762.17
  4829.5 1762.09  4853.7 1759.07  4871.2 1756.38  4877.9 1754.67  4883.3 1754.43
  4902.2 1752.02  4937.2 1750.08  4956.0 1748.50  4978.9 1748.03  4993.2 1747.17
  4993.7 1746.67  5001.8 1746.67  5002.3 1747.17  5022.3 1748.00  5043.1 1748.06
  5050.4 1748.73  5057.7 1750.36  5064.0 1750.48  5072.3 1751.60  5100.4 1752.74
  5172.3 1754.18  5207.7 1755.50  5243.1 1755.63  5343.1 1757.90  5500.4 1765.81
#Mann=3,-1,0
  4731.2    0.05       0  4993.2    0.03       0  5002.3    0.05       0
Bank Sta=4993.2,5002.3
Exp/Cntr=0.3,0.1

Type RM Length L Ch R = 1,9300,424,424,424
BEGIN DESCRIPTION:
Deadman 37 20.0
END DESCRIPTION:
XS GIS Cut Line= 3
      1647305.00      6914187.99      1647355.00      6914288.00
      1647755.00      6914688.00
#Sta/Elev= 30
  4892.8 1760.04  4895.6 1760.04  4901.2 1758.59  4906.8 1757.98  4920.8 1755.11
  4937.5 1750.52  4951.5 1745.85  4973.9 1746.24  4997.3 1744.58  4997.8 1744.08
  5005.9 1744.08  5006.4 1744.58  5008.1 1744.58  5032.9 1747.85  5061.2 1749.04
  5075.3 1749.98  5131.9 1750.69  5181.4 1752.24  5188.5 1752.12  5202.6 1752.53
  5216.7 1753.32  5273.3 1754.24  5329.9 1755.71  5400.6 1757.11  5443.0 1758.43
  5471.3 1760.48  5542.0 1764.02  5556.2 1764.79  5566.8 1765.81  5570.3 1765.81
#Mann=3,-1,0
  4892.8    0.05       0  4997.3    0.03       0  5006.4    0.05       0
Bank Sta=4997.3,5006.4
Exp/Cntr=0.3,0.1

Type RM Length L Ch R = 1,8876,442,442,442
BEGIN DESCRIPTION:
Deadman 37 19.0
END DESCRIPTION:
XS GIS Cut Line= 3
      1646954.98      6914387.96      1647005.00      6914488.00
      1647404.98      6914887.98
#Sta/Elev= 30
  4889.3 1759.04  4892.1 1759.04  4903.3 1757.48  4911.7 1755.41  4925.7 1752.83
  4948.0 1746.36  4956.4 1744.82  4964.8 1744.11  4978.8 1744.15  4987.2 1743.61
  4992.8 1743.64  4993.8 1743.38  4994.3 1742.88  5002.4 1742.88  5002.9 1743.38
  5029.4 1743.40  5043.6 1745.05  5057.7 1746.23  5100.1 1748.01  5142.6 1749.12
  5170.9 1749.33  5199.1 1750.25  5284.0 1751.64  5368.8 1753.50  5383.0 1754.41
  5397.1 1755.71  5411.3 1756.53  5453.7 1758.38  5552.7 1764.15  5566.8 1764.73
#Mann=3,-1,0
  4889.3    0.05       0  4993.8    0.03       0  5002.9    0.05       0
Bank Sta=4993.8,5002.9
Exp/Cntr=0.3,0.1

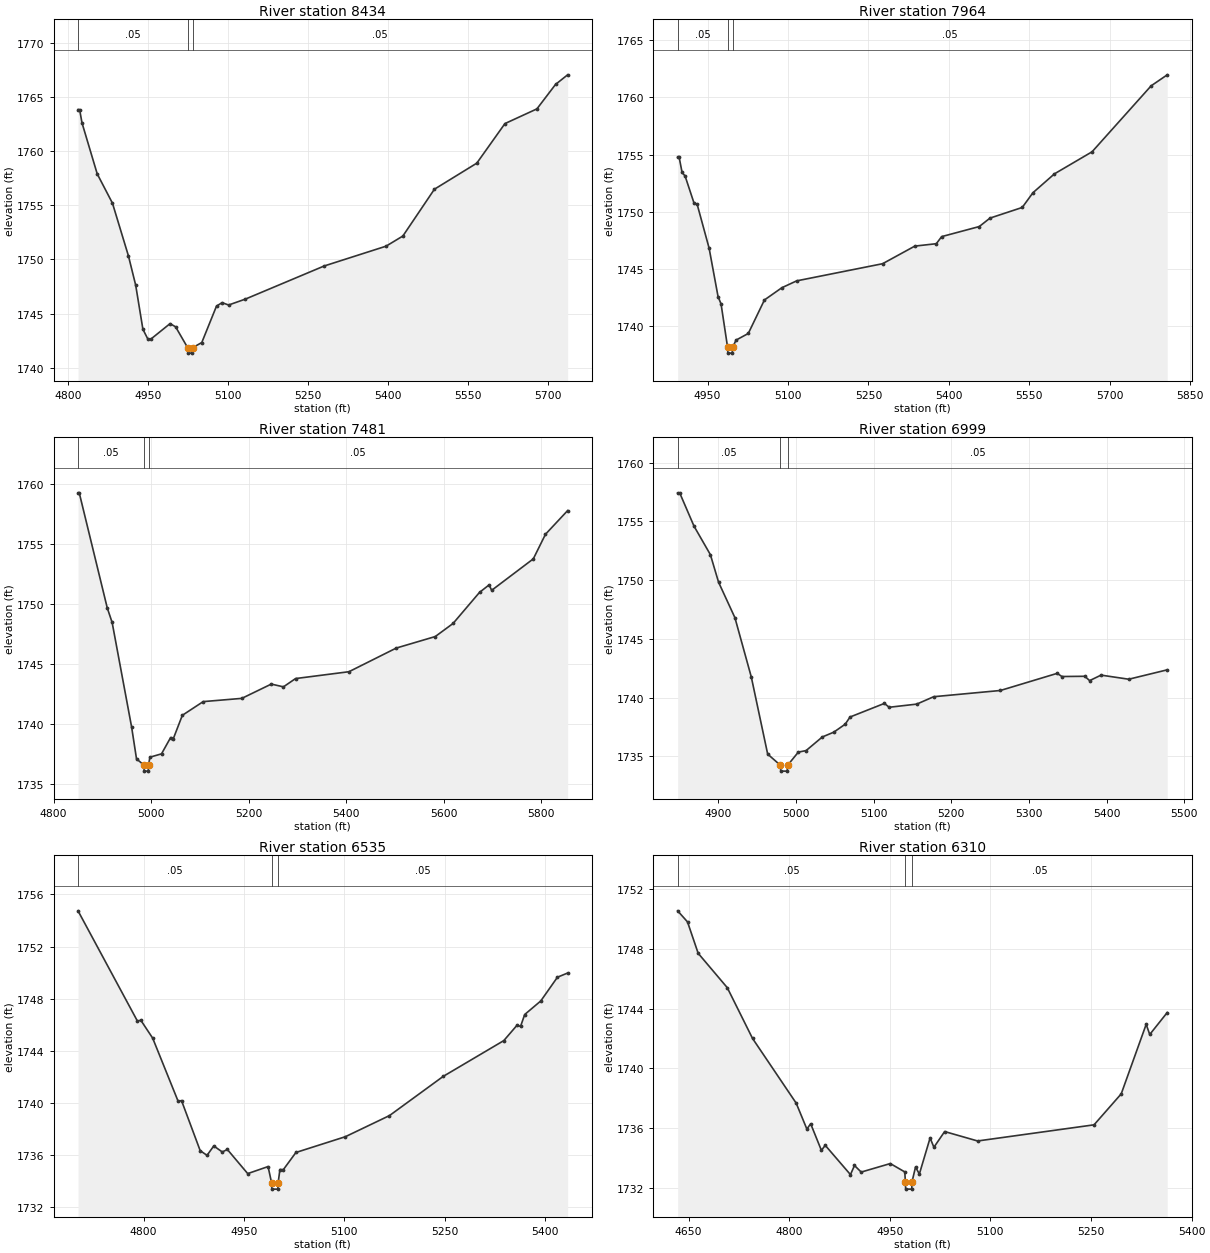
Type RM Length L Ch R = 1,8434,470,470,470
BEGIN DESCRIPTION:
Deadman 37 18.0
END DESCRIPTION:
XS GIS Cut Line= 3
      1646555.01      6914588.01      1646655.00      6914738.00
      1647305.00      6915088.00
#Sta/Elev= 30
  4818.2 1763.86  4821.2 1763.86  4825.7 1762.63  4854.2 1757.92  4882.8 1755.21
  4912.8 1750.33  4926.4 1747.62  4939.9 1743.55  4948.9 1742.67  4954.9 1742.64
  4990.9 1744.07  5001.3 1743.77  5023.9 1741.84  5024.4 1741.34  5032.6 1741.34
  5033.1 1741.84  5050.4 1742.32  5078.0 1745.69  5088.5 1746.01  5100.7 1745.79
  5132.3 1746.34  5280.0 1749.40  5396.0 1751.23  5427.6 1752.17  5486.8 1756.50
  5566.3 1758.91  5619.1 1762.57  5679.1 1763.93  5714.0 1766.19  5736.7 1767.08
#Mann=3,-1,0
  4818.2    0.05       0  5023.9    0.03       0  5033.1    0.05       0
Bank Sta=5023.9,5033.1
Exp/Cntr=0.3,0.1

Type RM Length L Ch R = 1,7964,483,483,483
BEGIN DESCRIPTION:
Deadman 37 17.0
END DESCRIPTION:
XS GIS Cut Line= 3
      1646255.04      6915038.02      1646355.00      6915088.00
      1647154.97      6915138.00
#Sta/Elev= 30
  4894.1 1754.77  4896.9 1754.77  4902.4 1753.44  4908.0 1753.13  4924.8 1750.74
  4930.4 1750.67  4952.8 1746.82  4969.5 1742.58  4975.1 1741.94  4987.3 1738.14
  4987.8 1737.64  4996.0 1737.64  4996.5 1738.14  5003.1 1738.78  5025.9 1739.36
  5056.0 1742.29  5088.5 1743.36  5116.1 1743.96  5276.4 1745.46  5336.5 1747.00
  5376.6 1747.21  5386.6 1747.83  5456.7 1748.71  5476.8 1749.45  5536.9 1750.38
  5556.9 1751.67  5597.0 1753.32  5667.2 1755.25  5777.4 1761.02  5807.4 1761.98
#Mann=3,-1,0
  4894.1    0.05       0  4987.3    0.03       0  4996.5    0.05       0
Bank Sta=4987.3,4996.5
Exp/Cntr=0.3,0.1

Type RM Length L Ch R = 1,7481,482,482,482
BEGIN DESCRIPTION:
Deadman 37 16.0
END DESCRIPTION:
XS GIS Cut Line= 3
      1646105.04      6915538.00      1646255.00      6915538.00
      1647055.04      6915237.98
#Sta/Elev= 30
  4850.2 1759.29  4852.7 1759.29  4910.2 1749.70  4920.2 1748.49  4960.2 1739.77
  4970.2 1737.13  4985.5 1736.61  4986.0 1736.11  4994.3 1736.11  4994.8 1736.61
  4997.7 1737.27  5021.5 1737.55  5040.2 1738.91  5045.5 1738.79  5064.2 1740.76
  5107.0 1741.90  5186.2 1742.17  5246.7 1743.36  5271.6 1743.13  5296.5 1743.82
  5406.0 1744.39  5503.0 1746.36  5583.1 1747.32  5619.6 1748.41  5673.9 1751.00
  5693.5 1751.62  5698.8 1751.17  5784.2 1753.79  5809.2 1755.84  5854.6 1757.81
#Mann=3,-1,0
  4850.2    0.05       0  4985.5    0.05       0  4994.8    0.05       0
Bank Sta=4985.5,4994.8
Exp/Cntr=0.3,0.1

Type RM Length L Ch R = 1,6999,464,464,464
BEGIN DESCRIPTION:
Deadman 37 15.0
END DESCRIPTION:
XS GIS Cut Line= 3
      1646205.00      6916038.00      1646355.00      6915988.00
      1646628.90      6915602.77
#Sta/Elev= 30
  4847.4 1757.44  4850.0 1757.44  4868.5 1754.60  4889.6 1752.17  4900.1 1749.83
  4921.2 1746.80  4942.3 1741.75  4963.4 1735.18  4979.8 1734.23  4980.3 1733.73
  4988.6 1733.73  4989.1 1734.23  5002.9 1735.35  5012.9 1735.48  5033.8 1736.64
  5048.6 1737.05  5063.3 1737.73  5069.5 1738.34  5113.8 1739.50  5119.9 1739.17
  5155.5 1739.44  5177.3 1740.07  5263.2 1740.60  5336.4 1742.06  5342.5 1741.79
  5372.0 1741.81  5378.2 1741.44  5392.9 1741.91  5428.6 1741.56  5478.2 1742.36
#Mann=3,-1,0
  4847.4    0.05       0  4979.8    0.03       0  4989.1    0.05       0
Bank Sta=4979.8,4989.1
Exp/Cntr=0.3,0.1

Type RM Length L Ch R = 1,6535,225,225,225
BEGIN DESCRIPTION:
Deadman 37 14.0
END DESCRIPTION:
XS GIS Cut Line= 3
      1646254.97      6916337.99      1646555.00      6916388.00
      1646955.03      6916237.99
#Sta/Elev= 30
  4702.1 1754.74  4790.8 1746.29  4795.9 1746.35  4813.6 1744.98  4851.7 1740.13
  4856.7 1740.19  4884.6 1736.35  4894.8 1735.99  4904.9 1736.71  4917.6 1736.25
  4925.2 1736.44  4955.6 1734.59  4986.0 1735.13  4991.2 1733.90  4991.7 1733.40
  5000.6 1733.40  5001.1 1733.90  5003.7 1734.90  5008.9 1734.90  5027.6 1736.21
  5101.5 1737.42  5167.4 1739.04  5247.5 1742.04  5338.2 1744.79  5357.8 1745.96
  5363.2 1745.88  5369.4 1746.79  5393.4 1747.83  5418.3 1749.65  5433.5 1749.97
#Mann=3,-1,0
  4702.1    0.05       0  4991.2    0.05       0  5001.1    0.05       0
Bank Sta=4991.2,5001.1
Exp/Cntr=0.3,0.1

Type RM Length L Ch R = 1,6310,256,256,256
BEGIN DESCRIPTION:
Mapping XS bf06c057
END DESCRIPTION:
XS GIS Cut Line= 3
      1646285.11      6916417.01      1646823.35      6916719.11
      1646929.97      6916683.00
#Sta/Elev= 30
  4633.8 1750.54  4648.5 1749.80  4664.4 1747.70  4707.8 1745.40  4745.4 1742.01
  4810.5 1737.68  4826.4 1735.95  4832.1 1736.30  4848.1 1734.52  4853.8 1734.86
  4891.4 1732.90  4897.4 1733.51  4907.4 1733.07  4950.8 1733.64  4972.4 1733.08
  4973.2 1732.43  4973.7 1731.93  4982.7 1731.93  4983.2 1732.43  4988.4 1733.41
  4994.1 1732.94  5010.1 1735.35  5015.8 1734.73  5031.8 1735.78  5080.9 1735.15
  5254.5 1736.23  5295.0 1738.30  5332.2 1742.95  5337.5 1742.27  5363.6 1743.74
#Mann=3,-1,0
  4633.8    0.05       0  4973.2    0.03       0  4983.2    0.05       0
Bank Sta=4973.2,4983.2
Exp/Cntr=0.3,0.1

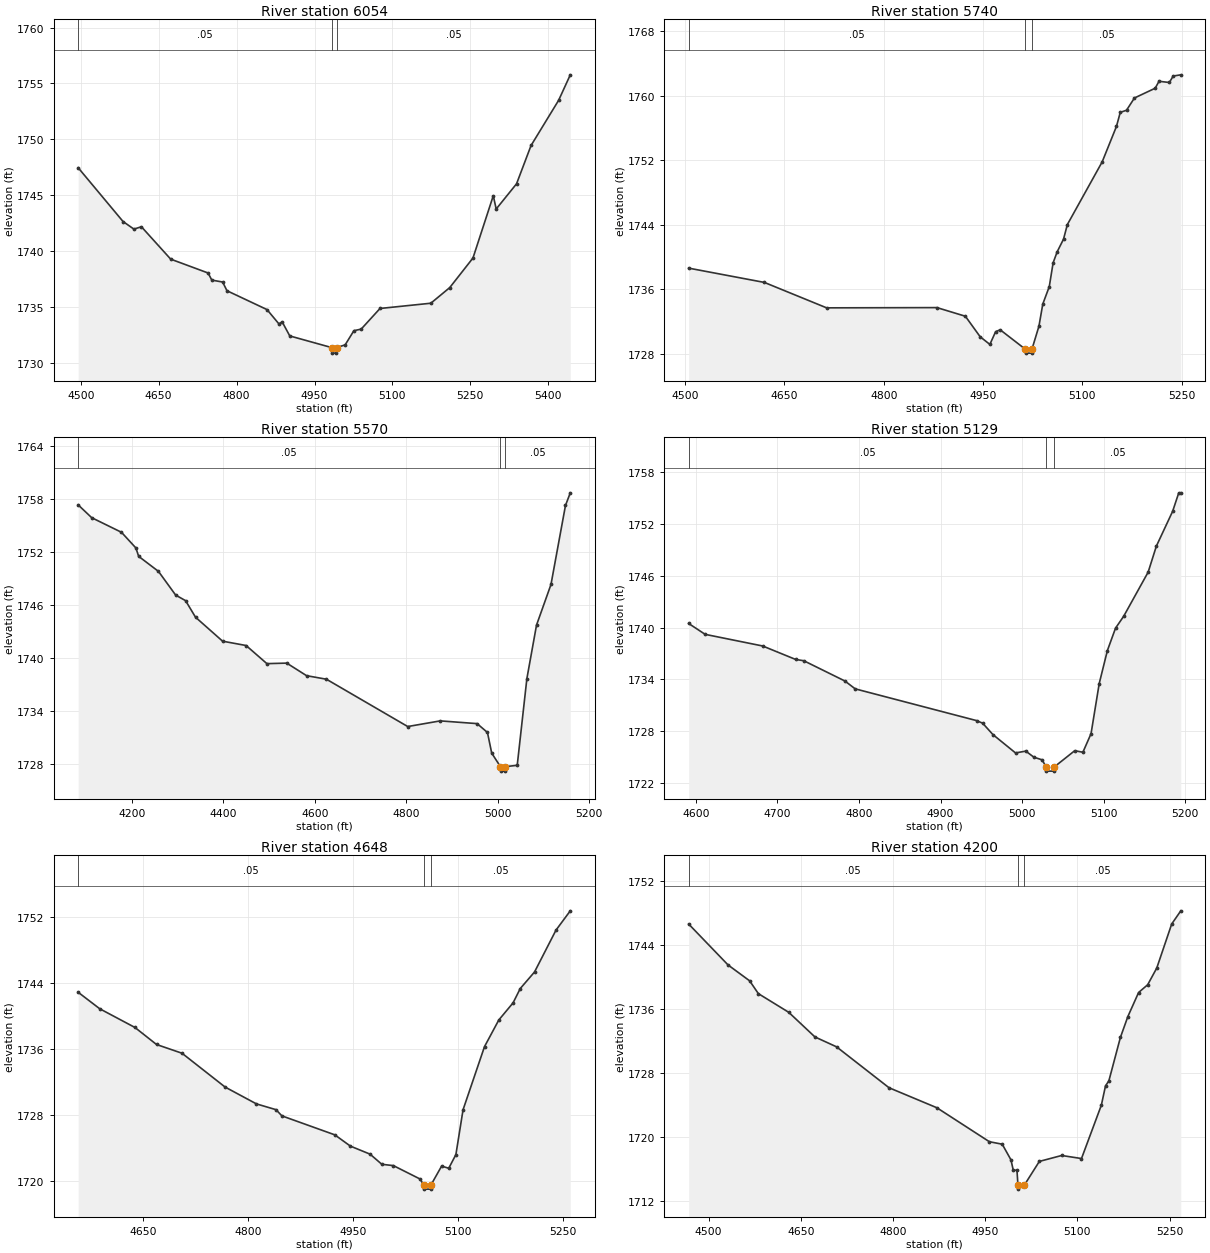
Type RM Length L Ch R = 1,6054,314,314,314
BEGIN DESCRIPTION:
Deadman 37 13.0
END DESCRIPTION:
XS GIS Cut Line= 3
      1646255.03      6916538.02      1646655.00      6916838.00
      1647055.02      6916637.99
#Sta/Elev= 30
  4495.1 1747.45  4581.5 1742.63  4602.4 1741.95  4616.9 1742.16  4673.2 1739.26
  4745.1 1738.02  4752.4 1737.38  4773.2 1737.21  4781.5 1736.43  4858.6 1734.74
  4881.5 1733.46  4887.8 1733.64  4902.4 1732.38  4982.8 1731.34  4983.3 1730.84
  4992.3 1730.84  4992.8 1731.34  5009.0 1731.58  5025.8 1732.85  5039.8 1732.99
  5076.1 1734.84  5173.9 1735.31  5210.3 1736.71  5255.0 1739.36  5294.1 1744.94
  5299.7 1743.75  5338.9 1746.01  5366.8 1749.44  5419.9 1753.49  5442.3 1755.77
#Mann=3,-1,0
  4495.1    0.05       0  4982.8    0.03       0  4992.8    0.05       0
Bank Sta=4982.8,4992.8
Exp/Cntr=0.3,0.1

Type RM Length L Ch R = 1,5740,170,170,170
BEGIN DESCRIPTION:
Mapping XS 6e67af77
END DESCRIPTION:
XS GIS Cut Line= 3
      1646379.06      6916774.43      1646563.95      6917053.07
      1646915.56      6917261.43
#Sta/Elev= 30
  4505.5 1738.63  4619.8 1736.86  4713.8 1733.71  4880.4 1733.74  4923.3 1732.67
  4945.7 1730.12  4960.3 1729.18  4969.0 1730.76  4975.9 1730.99  5013.6 1728.60
  5014.1 1728.10  5023.4 1728.10  5023.9 1728.60  5034.4 1731.44  5040.2 1734.18
  5050.0 1736.34  5055.8 1739.29  5062.0 1740.67  5071.5 1742.22  5077.3 1744.03
  5129.9 1751.80  5151.4 1756.18  5157.2 1757.93  5166.6 1758.19  5178.6 1759.71
  5209.9 1760.92  5215.7 1761.78  5231.3 1761.63  5237.1 1762.43  5248.6 1762.58
#Mann=3,-1,0
  4505.5    0.05       0  5013.6    0.05       0  5023.9    0.05       0
Bank Sta=5013.6,5023.9
Exp/Cntr=0.3,0.1

Type RM Length L Ch R = 1,5570,441,441,441
BEGIN DESCRIPTION:
Deadman 37 12.0
END DESCRIPTION:
XS GIS Cut Line= 3
      1646105.00      6916387.99      1646555.00      6917188.00
      1646605.00      6917338.00
#Sta/Elev= 30
  4082.4 1757.32  4112.0 1755.87  4177.1 1754.22  4208.6 1752.45  4214.7 1751.50
  4258.0 1749.80  4295.6 1747.12  4317.3 1746.49  4339.0 1744.62  4398.2 1741.91
  4449.6 1741.42  4495.1 1739.37  4538.5 1739.43  4581.8 1738.01  4625.2 1737.61
  4803.0 1732.26  4874.1 1732.90  4954.7 1732.59  4977.3 1731.59  4986.6 1729.26
  5005.7 1727.72  5006.2 1727.22  5015.5 1727.22  5016.0 1727.72  5042.4 1727.88
  5063.5 1737.68  5084.6 1743.73  5116.2 1748.32  5147.9 1757.25  5158.4 1758.68
#Mann=3,-1,0
  4082.4    0.05       0  5005.7    0.05       0  5016.0    0.05       0
Bank Sta=5005.7,5016
Exp/Cntr=0.3,0.1

Type RM Length L Ch R = 1,5129,481,481,481
BEGIN DESCRIPTION:
Deadman 37 11.0
END DESCRIPTION:
XS GIS Cut Line= 3
      1646205.01      6916737.96      1646155.00      6917138.00
      1646155.00      6917338.04
#Sta/Elev= 30
  4591.3 1740.48  4611.5 1739.22  4682.0 1737.87  4722.4 1736.31  4732.4 1736.16
  4782.8 1733.81  4795.4 1732.90  4944.1 1729.22  4951.6 1728.92  4964.2 1727.60
  4991.9 1725.47  5004.5 1725.68  5014.5 1724.97  5024.5 1724.67  5029.3 1723.86
  5029.8 1723.36  5039.1 1723.36  5039.6 1723.86  5064.5 1725.73  5074.5 1725.55
  5084.5 1727.71  5094.5 1733.52  5104.5 1737.34  5114.5 1739.94  5124.5 1741.32
  5154.5 1746.44  5164.5 1749.44  5184.5 1753.49  5192.0 1755.63  5194.5 1755.63
#Mann=3,-1,0
  4591.3    0.05       0  5029.3    0.05       0  5039.6    0.05       0
Bank Sta=5029.3,5039.6
Exp/Cntr=0.3,0.1

Type RM Length L Ch R = 1,4648,448,448,448
BEGIN DESCRIPTION:
Deadman 37 10.0
END DESCRIPTION:
XS GIS Cut Line= 3
      1645905.01      6916637.98      1645705.00      6917038.00
      1645655.00      6917288.01
#Sta/Elev= 30
  4557.7 1742.89  4588.5 1740.89  4638.8 1738.62  4669.5 1736.56  4705.9 1735.50
  4767.4 1731.40  4812.1 1729.36  4840.0 1728.66  4848.4 1727.91  4923.9 1725.61
  4946.2 1724.24  4974.2 1723.27  4991.0 1722.04  5007.5 1721.88  5045.7 1720.25
  5050.7 1719.53  5051.2 1719.03  5060.6 1719.03  5061.1 1719.53  5076.3 1721.82
  5086.5 1721.56  5096.7 1723.22  5106.9 1728.65  5137.5 1736.30  5157.9 1739.53
  5178.3 1741.61  5188.5 1743.34  5208.9 1745.35  5239.5 1750.42  5259.9 1752.76
#Mann=3,-1,0
  4557.7    0.05       0  5050.7    0.03       0  5061.1    0.05       0
Bank Sta=5050.7,5061.1
Exp/Cntr=0.3,0.1

Type RM Length L Ch R = 1,4200,444,444,444
BEGIN DESCRIPTION:
Deadman 37 9.0
END DESCRIPTION:
XS GIS Cut Line= 3
      1645655.02      6916487.98      1645305.00      6916888.00
      1645205.00      6917138.01
#Sta/Elev= 30
  4467.6 1746.61  4531.7 1741.50  4566.8 1739.52  4581.0 1737.92  4630.4 1735.59
  4673.1 1732.51  4708.2 1731.28  4793.6 1726.17  4871.5 1723.67  4956.9 1719.43
  4977.8 1719.12  4992.0 1717.17  4995.8 1715.87  5001.8 1715.87  5003.4 1714.01
  5003.9 1713.51  5013.8 1714.01  5038.2 1716.97  5074.5 1717.71  5106.8 1717.33
  5139.1 1723.99  5145.9 1726.41  5151.3 1727.02  5170.1 1732.45  5182.2 1735.05
  5199.7 1738.06  5214.5 1739.03  5229.3 1741.12  5253.6 1746.62  5268.4 1748.26
#Mann=3,-1,0
  4467.6    0.05       0  5003.4    0.05       0  5013.8    0.05       0
Bank Sta=5003.4,5013.8
Exp/Cntr=0.3,0.1

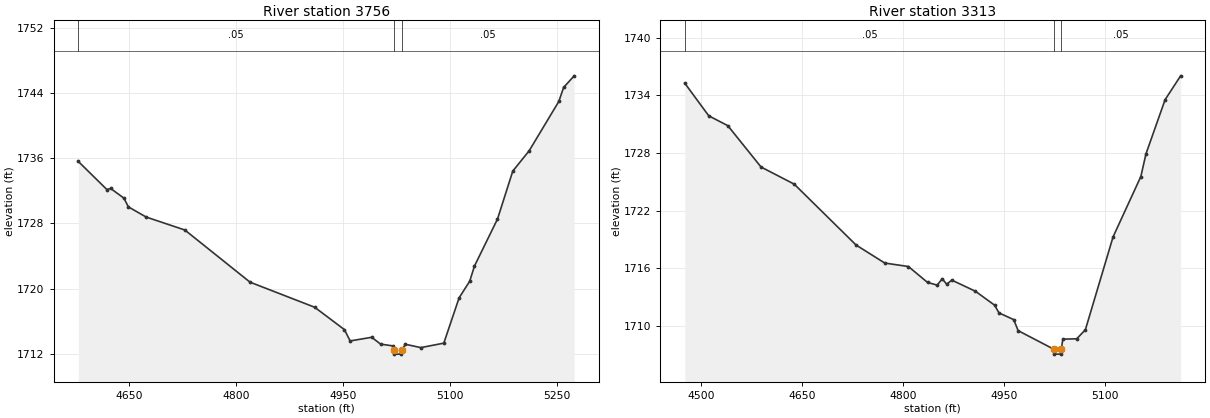
Type RM Length L Ch R = 1,3756,443,443,443
BEGIN DESCRIPTION:
Deadman 37 8.0
END DESCRIPTION:
XS GIS Cut Line= 3
      1645055.01      6916337.96      1644905.00      6916738.00
      1644805.00      6916988.00
#Sta/Elev= 30
  4578.3 1735.62  4618.4 1732.17  4623.7 1732.30  4642.4 1731.11  4648.6 1730.04
  4673.6 1728.79  4727.9 1727.20  4819.5 1720.79  4910.3 1717.71  4952.1 1714.96
  4960.1 1713.57  4990.4 1714.02  5002.9 1713.18  5020.3 1712.96  5021.8 1712.45
  5022.3 1711.95  5031.9 1711.95  5032.4 1712.45  5037.8 1713.16  5059.4 1712.75
  5091.7 1713.30  5113.2 1718.87  5128.1 1720.91  5134.8 1722.78  5167.1 1728.54
  5188.6 1734.44  5211.5 1736.92  5253.3 1743.00  5260.0 1744.71  5274.8 1746.14
#Mann=3,-1,0
  4578.3    0.05       0  5021.8    0.03       0  5032.4    0.05       0
Bank Sta=5021.8,5032.4
Exp/Cntr=0.3,0.1

Type RM Length L Ch R = 1,3313,465,465,465
BEGIN DESCRIPTION:
Deadman 37 7.0
END DESCRIPTION:
XS GIS Cut Line= 3
      1644904.99      6916238.01      1644505.00      6916588.00
      1644455.01      6916787.96
#Sta/Elev= 30
  4475.3 1735.28  4510.9 1731.88  4539.3 1730.85  4588.7 1726.54  4638.1 1724.75
  4730.1 1718.40  4772.8 1716.52  4807.9 1716.16  4836.4 1714.50  4850.7 1714.22
  4858.3 1714.88  4864.9 1714.31  4872.5 1714.74  4907.6 1713.58  4936.1 1712.13
  4942.7 1711.32  4964.6 1710.62  4971.2 1709.47  5024.6 1707.52  5025.1 1707.02
  5034.8 1707.02  5035.3 1707.52  5037.7 1708.58  5058.3 1708.62  5071.2 1709.56
  5112.4 1719.25  5153.7 1725.54  5161.4 1727.92  5189.8 1733.56  5212.9 1736.05
#Mann=3,-1,0
  4475.3    0.05       0  5024.6    0.05       0  5035.3    0.05       0
Bank Sta=5024.6,5035.3
Exp/Cntr=0.3,0.1