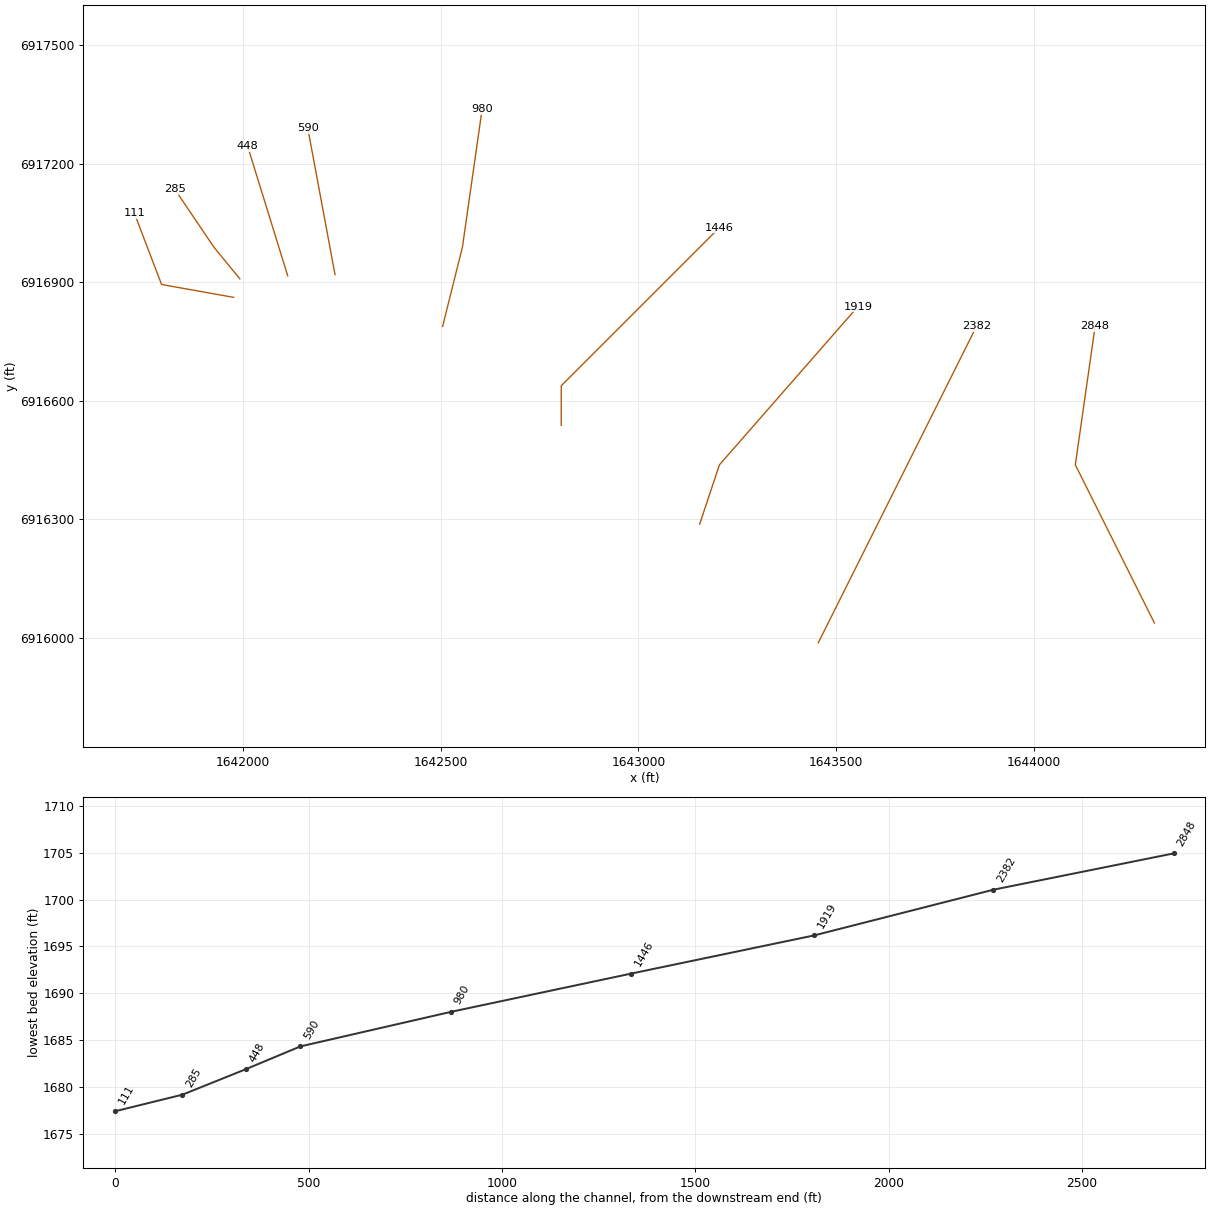
HEC-RAS study Deadman 37.prj: Deadman 37 Base Level Engineering

--- Deadman 37.g01 (geometry) --- (continued)

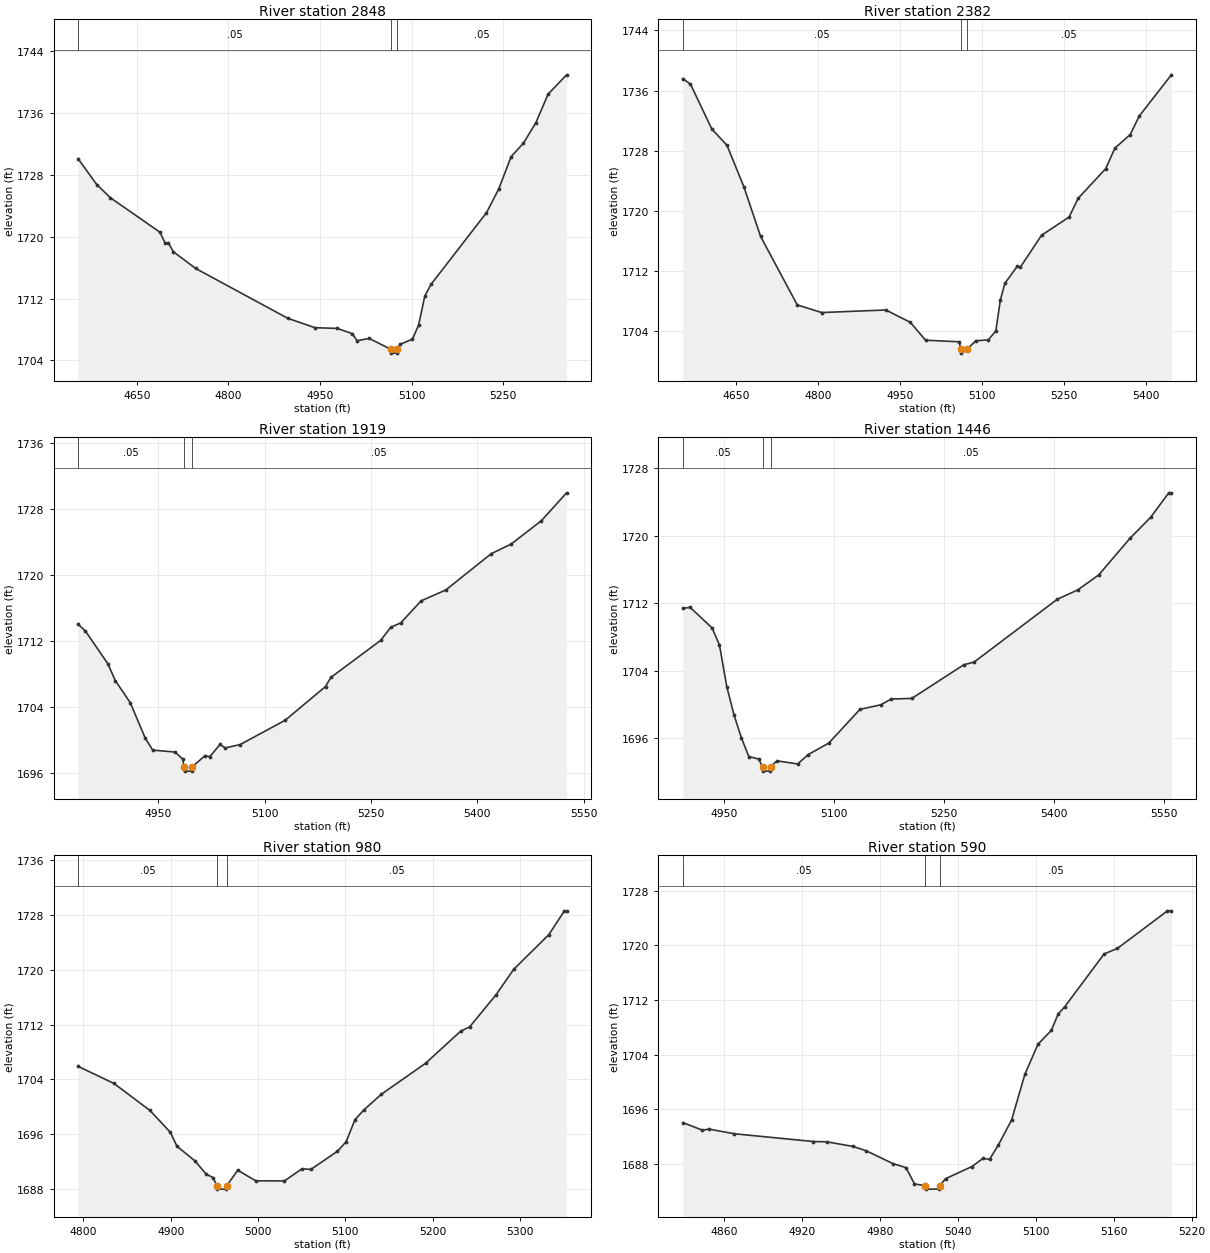
Type RM Length L Ch R = 1,2848,466,466,466
BEGIN DESCRIPTION:
Deadman 37 6.0
END DESCRIPTION:
XS GIS Cut Line= 3
      1644305.00      6916037.99      1644105.00      6916438.00
      1644155.00      6916788.03
#Sta/Elev= 30
  4553.3 1730.13  4584.1 1726.77  4606.4 1725.06  4687.5 1720.61  4695.9 1719.24
  4701.4 1719.22  4709.8 1718.06  4746.2 1715.91  4897.1 1709.46  4941.8 1708.24
  4978.2 1708.15  5003.0 1707.47  5010.6 1706.56  5030.8 1706.85  5065.9 1705.45
  5066.4 1704.95  5076.1 1704.95  5076.6 1705.45  5081.3 1706.09  5101.5 1706.76
  5111.6 1708.59  5121.7 1712.33  5131.8 1713.84  5222.8 1723.12  5243.0 1726.21
  5263.2 1730.38  5283.4 1732.13  5303.6 1734.75  5323.8 1738.47  5354.1 1740.97
#Mann=3,-1,0
  4553.3    0.05       0  5065.9    0.03       0  5076.6    0.05       0
Bank Sta=5065.9,5076.6
Exp/Cntr=0.3,0.1

Type RM Length L Ch R = 1,2382,463,463,463
BEGIN DESCRIPTION:
Deadman 37 5.0
END DESCRIPTION:
XS GIS Cut Line= 3
      1643455.01      6915988.01      1643655.00      6916388.00
      1643854.99      6916787.99
#Sta/Elev= 30
  4552.2 1737.59  4566.2 1736.87  4605.3 1730.90  4633.2 1728.71  4664.0 1723.21
  4694.7 1716.59  4761.8 1707.48  4806.5 1706.47  4923.9 1706.81  4968.7 1705.17
  4996.6 1702.79  5058.1 1702.58  5061.1 1701.57  5061.6 1701.07  5071.9 1701.57
  5088.8 1702.72  5111.2 1702.82  5125.2 1704.02  5133.6 1708.16  5141.9 1710.36
  5164.3 1712.61  5169.9 1712.48  5209.0 1716.76  5259.3 1719.17  5276.1 1721.68
  5326.4 1725.62  5343.2 1728.35  5371.1 1730.14  5387.9 1732.63  5446.6 1738.10
#Mann=3,-1,0
  4552.2    0.05       0  5061.1    0.03       0  5071.9    0.05       0
Bank Sta=5061.1,5071.9
Exp/Cntr=0.3,0.1

Type RM Length L Ch R = 1,1919,473,473,473
BEGIN DESCRIPTION:
Deadman 37 4.0
END DESCRIPTION:
XS GIS Cut Line= 3
      1643154.99      6916287.97      1643205.00      6916438.00
      1643555.03      6916838.04
#Sta/Elev= 30
  4836.4 1714.01  4847.0 1713.16  4878.6 1709.20  4889.1 1707.16  4910.2 1704.49
  4931.3 1700.20  4941.8 1698.74  4973.5 1698.50  4984.0 1697.66  4986.5 1696.69
  4987.0 1696.19  4996.9 1696.19  4997.4 1696.69  5015.9 1698.08  5022.5 1697.94
  5036.8 1699.42  5044.4 1699.00  5065.3 1699.41  5128.8 1702.35  5185.8 1706.44
  5193.4 1707.55  5263.6 1712.03  5277.9 1713.62  5292.1 1714.16  5320.6 1716.82
  5355.7 1718.15  5419.7 1722.54  5447.7 1723.70  5490.5 1726.54  5526.1 1729.92
#Mann=3,-1,0
  4836.4    0.05       0  4986.5    0.05       0  4997.4    0.05       0
Bank Sta=4986.5,4997.4
Exp/Cntr=0.3,0.1

Type RM Length L Ch R = 1,1446,466,466,466
BEGIN DESCRIPTION:
Deadman 37 3.0
END DESCRIPTION:
XS GIS Cut Line= 3
      1642805.00      6916538.03      1642805.00      6916638.00
      1643205.03      6917038.03
#Sta/Elev= 30
  4894.2 1711.39  4904.2 1711.52  4934.2 1709.07  4944.2 1707.05  4954.2 1702.10
  4964.2 1698.72  4974.2 1696.02  4984.2 1693.84  4997.7 1693.54  5002.9 1692.61
  5003.4 1692.11  5013.3 1692.11  5013.8 1692.61  5022.5 1693.33  5050.7 1692.96
  5064.9 1694.06  5093.2 1695.44  5135.6 1699.43  5163.9 1699.97  5178.0 1700.65
  5206.3 1700.73  5277.0 1704.71  5291.2 1705.04  5404.3 1712.47  5432.6 1713.60
  5460.9 1715.36  5503.3 1719.68  5531.6 1722.18  5556.3 1725.09  5559.9 1725.09
#Mann=3,-1,0
  4894.2    0.05       0  5002.9    0.05       0  5013.8    0.05       0
Bank Sta=5002.9,5013.8
Exp/Cntr=0.3,0.1

Type RM Length L Ch R = 1,980,390,390,390
BEGIN DESCRIPTION:
Deadman 37 2.0
END DESCRIPTION:
XS GIS Cut Line= 3
      1642505.00      6916788.00      1642555.00      6916988.00
      1642605.00      6917337.99
#Sta/Elev= 30
  4793.8 1705.92  4835.0 1703.42  4876.3 1699.48  4899.5 1696.32  4907.2 1694.27
  4927.8 1692.13  4940.7 1690.20  4948.4 1689.71  4953.1 1688.52  4953.6 1688.02
  4963.8 1688.02  4964.3 1688.52  4976.8 1690.78  4997.4 1689.23  5030.3 1689.22
  5050.5 1690.99  5060.6 1690.89  5090.9 1693.53  5101.0 1694.92  5111.1 1698.14
  5121.2 1699.55  5141.4 1701.85  5191.9 1706.35  5232.3 1711.05  5242.4 1711.65
  5272.7 1716.34  5292.9 1720.04  5333.3 1725.12  5351.0 1728.57  5353.5 1728.57
#Mann=3,-1,0
  4793.8    0.05       0  4953.1    0.03       0  4964.3    0.05       0
Bank Sta=4953.1,4964.3
Exp/Cntr=0.3,0.1

Type RM Length L Ch R = 1,590,142,142,142
BEGIN DESCRIPTION:
Mapping XS 632a94f7
END DESCRIPTION:
XS GIS Cut Line= 2
      1642232.93      6916919.08      1642164.07      6917288.92
#Sta/Elev= 30
  4828.1 1694.07  4843.2 1692.95  4848.3 1693.11  4867.7 1692.43  4928.7 1691.29
  4938.9 1691.25  4959.2 1690.57  4969.4 1689.93  4989.8 1688.07  4999.9 1687.47
  5006.5 1685.09  5014.7 1684.82  5015.2 1684.32  5025.4 1684.32  5025.9 1684.82
  5030.4 1685.85  5050.8 1687.63  5059.2 1688.82  5064.3 1688.68  5071.1 1690.79
  5081.3 1694.46  5091.5 1701.13  5101.6 1705.54  5111.8 1707.55  5117.1 1709.95
  5122.2 1711.03  5152.5 1718.76  5162.7 1719.56  5201.3 1725.07  5204.3 1725.07
#Mann=3,-1,0
  4828.1    0.05       0  5014.7    0.05       0  5025.9    0.05       0
Bank Sta=5014.7,5025.9
Exp/Cntr=0.3,0.1

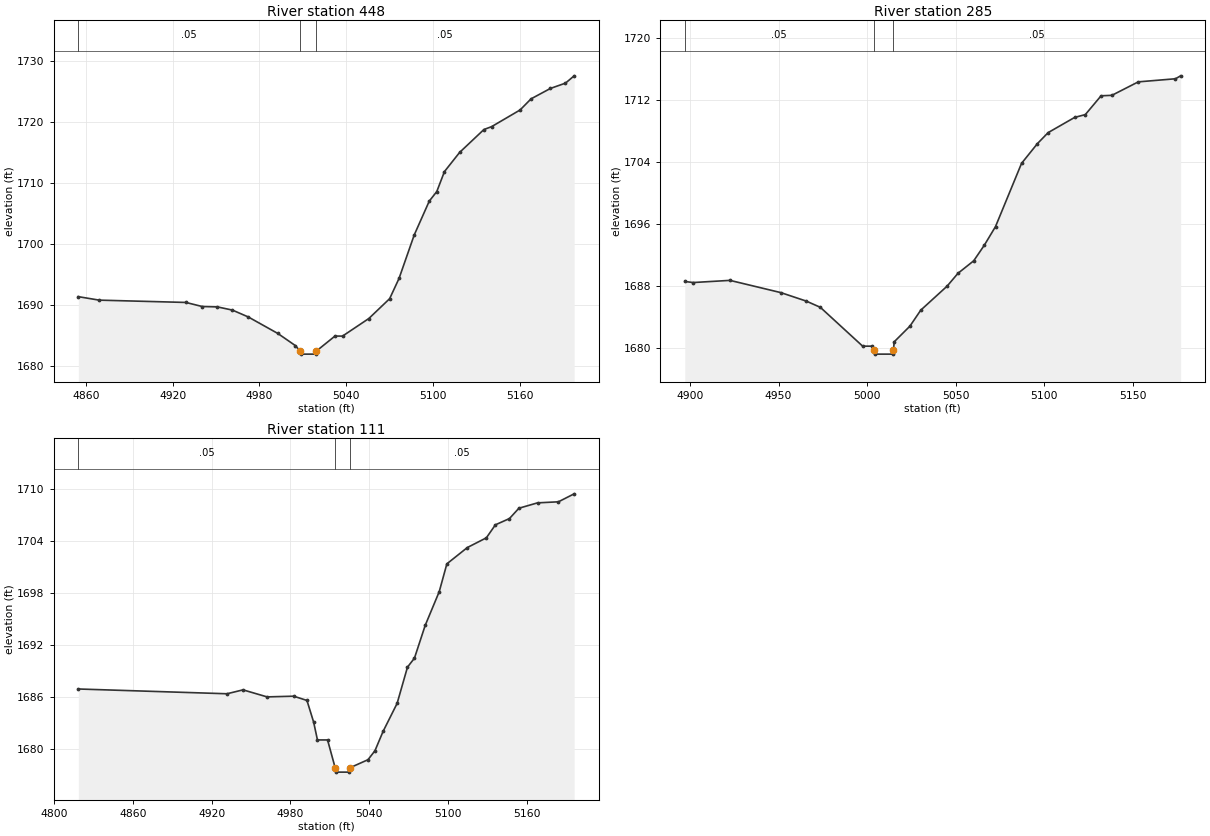
Type RM Length L Ch R = 1,448,163,163,163
BEGIN DESCRIPTION:
Mapping XS 30dc00a7
END DESCRIPTION:
XS GIS Cut Line= 2
      1642113.29      6916916.12      1642011.90      6917243.69
#Sta/Elev= 30
  4854.8 1691.31  4869.2 1690.74  4929.2 1690.36  4940.5 1689.69  4951.0 1689.63
  4961.4 1689.10  4972.3 1687.98  4992.8 1685.26  5004.9 1683.27  5008.2 1682.37
  5008.7 1681.87  5018.9 1681.87  5019.4 1682.37  5032.3 1684.84  5037.5 1684.83
  5055.7 1687.72  5070.1 1690.98  5076.6 1694.31  5087.1 1701.45  5097.5 1707.01
  5102.7 1708.58  5108.0 1711.86  5118.5 1715.01  5135.3 1718.77  5140.6 1719.24
  5160.3 1721.98  5167.9 1723.81  5181.3 1725.52  5191.7 1726.39  5197.7 1727.59
#Mann=3,-1,0
  4854.8    0.05       0  5008.2    0.05       0  5019.4    0.05       0
Bank Sta=5008.2,5019.4
Exp/Cntr=0.3,0.1

Type RM Length L Ch R = 1,285,174,174,174
BEGIN DESCRIPTION:
Mapping XS 1b046ddd
END DESCRIPTION:
XS GIS Cut Line= 3
      1641992.18      6916908.36      1641927.08      6916987.78
      1641827.89      6917134.63
#Sta/Elev= 30
  4897.1 1688.55  4901.8 1688.41  4922.6 1688.69  4951.3 1687.11  4965.7 1686.01
  4973.6 1685.21  4997.5 1680.19  5002.9 1680.19  5003.7 1679.66  5004.2 1679.16
  5014.4 1679.16  5014.9 1679.66  5015.3 1680.75  5024.2 1682.78  5030.3 1684.84
  5045.2 1687.95  5051.3 1689.60  5060.2 1691.22  5066.2 1693.24  5072.5 1695.64
  5087.2 1703.81  5096.2 1706.37  5102.2 1707.78  5117.2 1709.75  5123.2 1710.11
  5132.1 1712.54  5138.2 1712.60  5153.1 1714.34  5174.1 1714.74  5177.0 1715.12
#Mann=3,-1,0
  4897.1    0.05       0  5003.7    0.05       0  5014.9    0.05       0
Bank Sta=5003.7,5014.9
Exp/Cntr=0.3,0.1

Type RM Length L Ch R = 1,111,0,0,0
BEGIN DESCRIPTION:
Deadman 37 1.0
END DESCRIPTION:
XS GIS Cut Line= 3
      1641976.53      6916861.48      1641794.27      6916894.03
      1641725.63      6917074.04
#Sta/Elev= 30
  4818.4 1686.97  4931.7 1686.42  4943.9 1686.87  4962.2 1686.06  4982.5 1686.14
  4992.6 1685.65  4997.7 1683.15  5000.6 1681.10  5008.3 1681.10  5014.1 1677.89
  5014.6 1677.39  5024.8 1677.39  5025.3 1677.89  5039.1 1678.82  5044.4 1679.85
  5050.6 1682.08  5061.3 1685.31  5069.2 1689.49  5074.5 1690.52  5082.7 1694.30
  5093.4 1698.19  5099.2 1701.39  5114.8 1703.27  5129.3 1704.39  5136.2 1705.89
  5146.9 1706.61  5154.1 1707.80  5168.3 1708.42  5184.2 1708.54  5196.2 1709.46
#Mann=3,-1,0
  4818.4    0.05       0  5014.1    0.05       0  5025.3    0.05       0
Bank Sta=5014.1,5025.3
Exp/Cntr=0.3,0.1

Chan Stop Cuts=-1