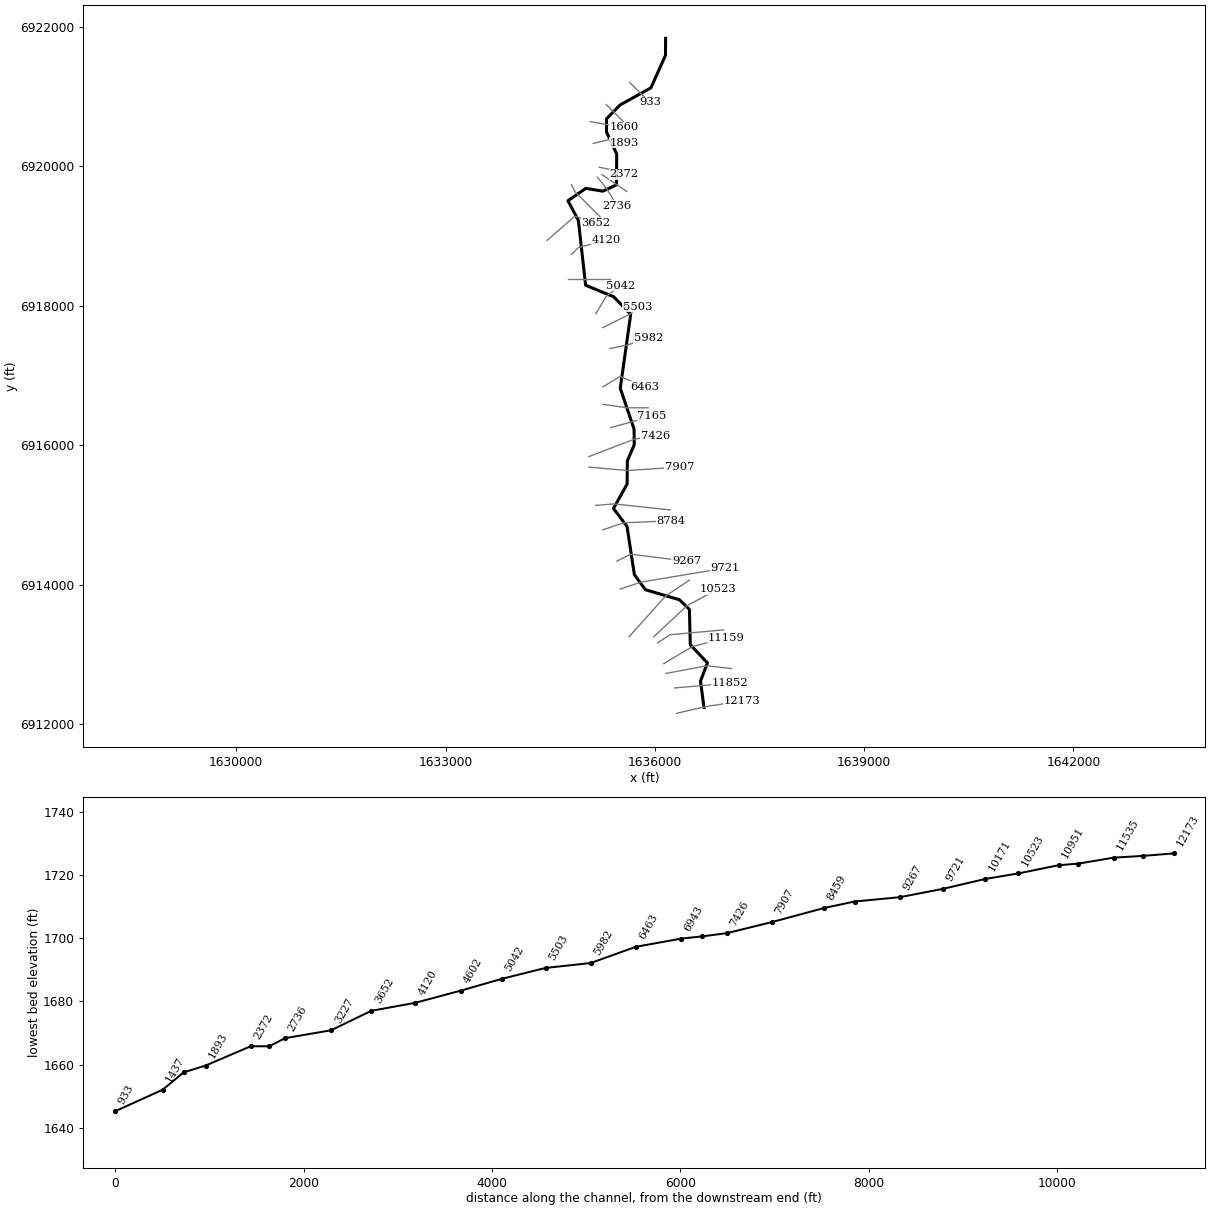
--- Deadman 38.prj (project) ---

Proj Title=Deadman 38 Base Level Engineering
Current Plan=p01
Default Exp/Contr=0.3,0.1
English Units
Geom File=g01
Flow File=f01
Plan File=p01
BEGIN DESCRIPTION:
Deadman 38
END DESCRIPTION:

--- Deadman 38.p01 (plan) ---

Plan Title=Multiple Run
Short Identifier=Multiple
Geom File=g01
Flow File=f01
Subcritical Flow
K Sum by GR= 0
Std Step Tol= 0.01
Critical Tol= 0.01
Num of Std Step Trials= 20
Max Error Tol= 0.3
Flow Tol Ratio= 0.001
Split Flow NTrial= 30
Split Flow Tol= 0.02
Split Flow Ratio= 0.02
Log Output Level= 0
Friction Slope Method= 1
Unsteady Friction Slope Method= 2
Unsteady Bridges Friction Slope Method= 1
Parabolic Critical Depth
Global Vel Dist=  1 , 1 , 1
Global Log Level= 0
CheckData=True
Encroach Param= -1, 0, 0, 0
BEGIN DESCRIPTION:
Multiple Run
END DESCRIPTION:

--- Deadman 38.f01 (steady flow) ---

Flow Title=Multiple
Number of Profiles=7
Profile Names=10-year,25-year,50-year,1pct_min,100-year,1pct_plu,500-year
River Rch & RM= Deadman 38,Reach-1,12173
     183     247     297     179     356     711     518
River Rch & RM= Deadman 38,Reach-1,11852
     328     457     564     347     692    1380    1054
River Rch & RM= Deadman 38,Reach-1,5042
     372     523     650     401     801    1598    1232
Boundary for River Rch & Prof#=Deadman 38,Reach-1,1
Up Type=0
Dn Type=3
Dn Slope=0.01
Boundary for River Rch & Prof#=Deadman 38,Reach-1,2
Up Type=0
Dn Type=3
Dn Slope=0.01
Boundary for River Rch & Prof#=Deadman 38,Reach-1,3
Up Type=0
Dn Type=3
Dn Slope=0.01
Boundary for River Rch & Prof#=Deadman 38,Reach-1,4
Up Type=0
Dn Type=3
Dn Slope=0.01
Boundary for River Rch & Prof#=Deadman 38,Reach-1,5
Up Type=0
Dn Type=3
Dn Slope=0.01
Boundary for River Rch & Prof#=Deadman 38,Reach-1,6
Up Type=0
Dn Type=3
Dn Slope=0.01
Boundary for River Rch & Prof#=Deadman 38,Reach-1,7
Up Type=0
Dn Type=3
Dn Slope=0.01

--- Deadman 38.g01 (geometry) ---

Geom Title=Existing Conditions

River Reach=Deadman 38,Reach-1
Reach XY= 30
      1636705.00      6912238.00      1636654.89      6912617.91
      1636754.07      6912877.52      1636508.48      6913139.26
      1636495.87      6913644.74      1636353.50      6913784.39
      1635865.62      6913927.95      1635707.06      6914143.85
      1635601.46      6914836.54      1635407.14      6915093.97
      1635602.94      6915443.85      1635606.22      6915777.50
      1635704.93      6916008.03      1635702.74      6916232.06
      1635504.64      6916817.85      1635653.95      6917877.56
      1635411.17      6918130.12      1635008.07      6918296.28
      1634903.94      6919227.56      1634754.64      6919508.21
      1635010.94      6919685.74      1635255.00      6919645.56
      1635449.66      6919735.26      1635453.78      6920177.50
      1635307.24      6920493.93      1635307.06      6920682.15
      1635498.83      6920880.14      1635944.24      6921128.32
      1636152.74      6921593.94      1636155.00      6921838.00

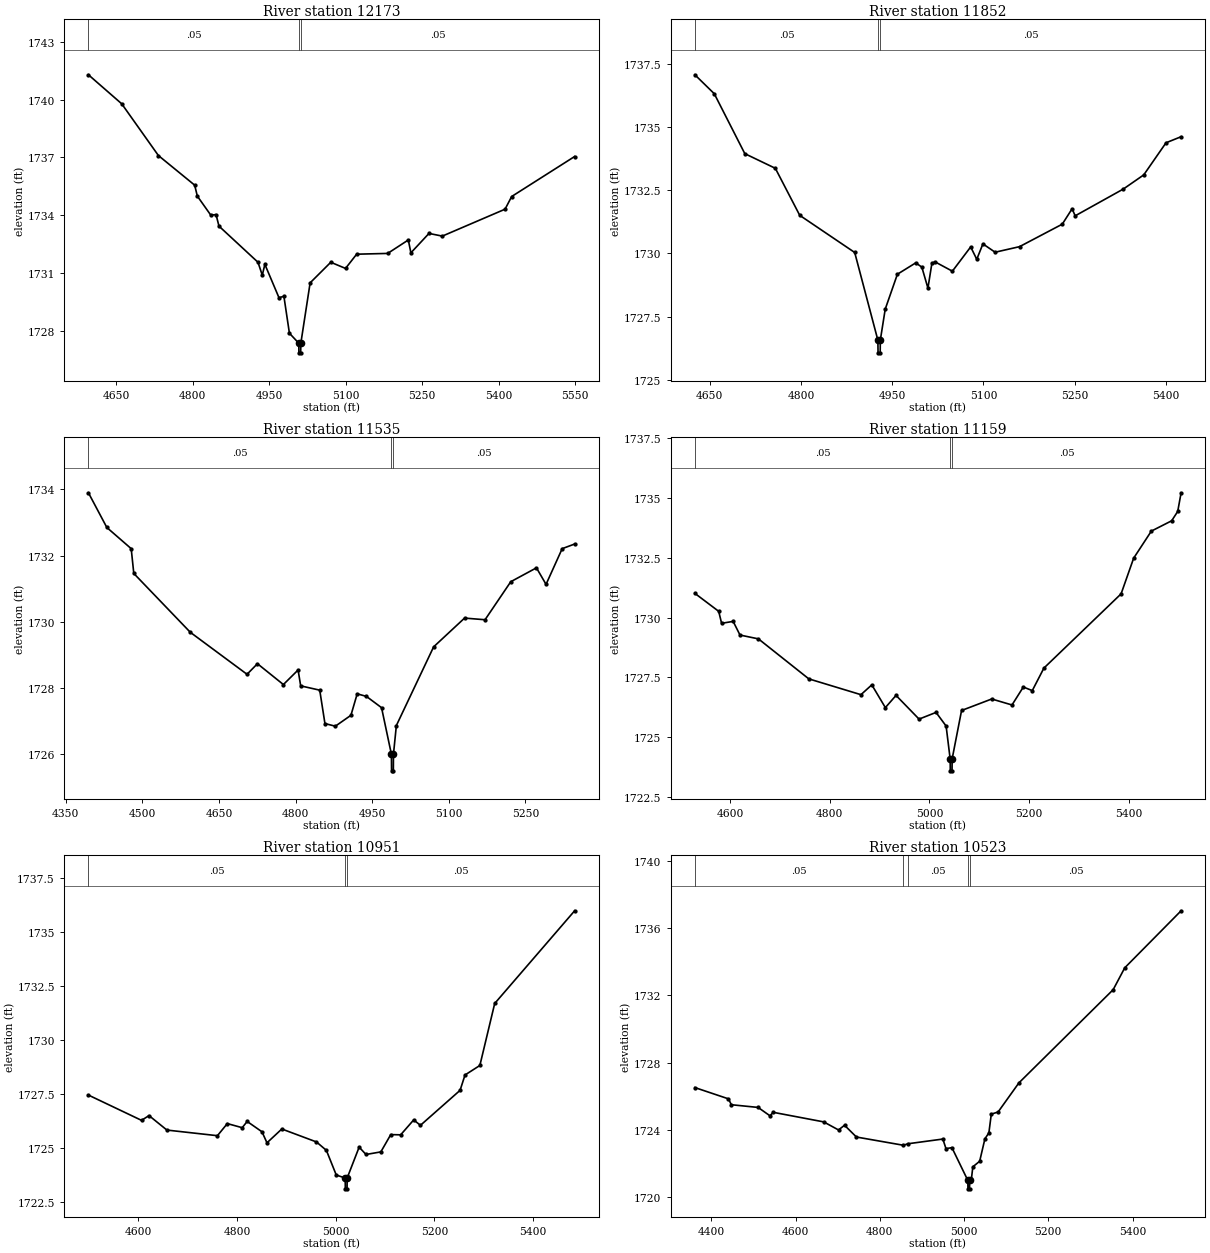
Type RM Length L Ch R = 1,12173,321,321,321
BEGIN DESCRIPTION:
Deadman 38 25.0
END DESCRIPTION:
XS GIS Cut Line= 3
      1636311.40      6912154.42      1636699.89      6912245.58
      1637246.76      6912334.55
#Sta/Elev= 30
  4595.8 1741.30  4661.1 1739.79  4733.0 1737.10  4804.1 1735.56  4809.3 1734.99
  4835.7 1734.00  4846.0 1734.03  4851.7 1733.43  4928.2 1731.55  4936.6 1730.88
  4941.7 1731.44  4969.3 1729.71  4979.0 1729.78  4989.8 1727.86  5008.2 1727.34
  5008.4 1726.84  5011.9 1726.84  5012.2 1727.34  5030.4 1730.48  5070.9 1731.55
  5099.8 1731.23  5121.6 1731.97  5182.4 1732.01  5222.9 1732.71  5227.9 1732.04
  5263.4 1733.05  5289.5 1732.91  5412.5 1734.31  5425.5 1734.97  5548.9 1737.05
#Mann=3,-1,0
  4595.8    0.05       0  5008.2    0.03       0  5012.2    0.05       0
Bank Sta=5008.2,5012.2
Exp/Cntr=0.3,0.1

Type RM Length L Ch R = 1,11852,317,317,317
BEGIN DESCRIPTION:
Mapping XS b94d4c4a
END DESCRIPTION:
XS GIS Cut Line= 2
      1636283.21      6912519.02      1637079.69      6912588.46
#Sta/Elev= 30
  4625.5 1737.07  4657.4 1736.32  4707.6 1733.95  4757.8 1733.37  4797.9 1731.51
  4888.3 1730.04  4926.4 1726.57  4926.7 1726.07  4930.2 1726.07  4930.4 1726.57
  4938.5 1727.80  4958.5 1729.18  4988.7 1729.63  4998.7 1729.46  5008.7 1728.63
  5015.2 1729.61  5020.3 1729.67  5048.9 1729.30  5079.0 1730.26  5089.0 1729.77
  5099.1 1730.38  5119.2 1730.05  5159.3 1730.27  5229.6 1731.16  5245.8 1731.77
  5250.8 1731.49  5330.0 1732.55  5363.6 1733.11  5400.2 1734.38  5425.0 1734.62
#Mann=3,-1,0
  4625.5    0.05       0  4926.4    0.03       0  4930.4    0.05       0
Bank Sta=4926.4,4930.4
Exp/Cntr=0.3,0.1

Type RM Length L Ch R = 1,11535,376,376,376
BEGIN DESCRIPTION:
Deadman 38 24.0
END DESCRIPTION:
XS GIS Cut Line= 3
      1636159.49      6912727.34      1636755.00      6912838.00
      1637099.24      6912796.79
#Sta/Elev= 30
  4394.2 1733.90  4430.3 1732.85  4478.0 1732.21  4483.1 1731.46  4593.8 1729.68
  4704.9 1728.41  4725.3 1728.73  4776.1 1728.10  4804.9 1728.54  4810.0 1728.06
  4847.3 1727.93  4857.5 1726.92  4877.9 1726.84  4908.4 1727.17  4920.7 1727.82
  4938.9 1727.74  4968.4 1727.40  4987.7 1725.99  4988.0 1725.49  4991.5 1725.49
  4991.7 1725.99  4997.4 1726.86  5070.4 1729.24  5131.0 1730.11  5171.1 1730.06
  5221.5 1731.21  5271.8 1731.63  5290.6 1731.13  5322.2 1732.21  5346.6 1732.35
#Mann=3,-1,0
  4394.2    0.05       0  4987.7    0.03       0  4991.7    0.05       0
Bank Sta=4987.7,4991.7
Exp/Cntr=0.3,0.1

Type RM Length L Ch R = 1,11159,208,208,208
BEGIN DESCRIPTION:
Deadman 38 23.0
END DESCRIPTION:
XS GIS Cut Line= 3
      1636129.13      6912868.40      1636534.96      6913111.46
      1637021.60      6913236.91
#Sta/Elev= 30
  4529.4 1731.01  4577.2 1730.26  4583.0 1729.76  4606.2 1729.84  4619.9 1729.27
  4656.9 1729.11  4758.0 1727.44  4862.6 1726.78  4884.4 1727.19  4911.6 1726.24
  4933.0 1726.75  4979.2 1725.76  5013.3 1726.04  5033.5 1725.47  5041.6 1724.10
  5041.9 1723.60  5045.4 1723.60  5045.6 1724.10  5064.5 1726.12  5125.0 1726.60
  5165.7 1726.35  5188.4 1727.10  5206.4 1726.95  5229.7 1727.89  5384.6 1730.99
  5409.8 1732.48  5445.3 1733.61  5486.0 1734.04  5498.2 1734.43  5505.0 1735.21
#Mann=3,-1,0
  4529.4    0.05       0  5041.6    0.03       0  5045.6    0.05       0
Bank Sta=5041.6,5045.6
Exp/Cntr=0.3,0.1

Type RM Length L Ch R = 1,10951,428,428,428
BEGIN DESCRIPTION:
Mapping XS 4a51e032
END DESCRIPTION:
XS GIS Cut Line= 3
      1636037.96      6913165.69      1636220.29      6913282.91
      1636986.39      6913352.35
#Sta/Elev= 30
  4498.5 1727.44  4606.2 1726.27  4621.4 1726.49  4657.7 1725.82  4760.1 1725.56
  4780.2 1726.12  4810.4 1725.93  4820.4 1726.22  4850.5 1725.74  4860.6 1725.23
  4890.7 1725.87  4961.0 1725.27  4981.1 1724.88  5001.1 1723.74  5019.2 1723.60
  5019.5 1723.10  5023.0 1723.10  5023.2 1723.60  5047.5 1725.03  5061.4 1724.69
  5091.5 1724.81  5111.6 1725.61  5131.7 1725.60  5158.1 1726.29  5171.8 1726.04
  5252.2 1727.66  5262.2 1728.37  5292.3 1728.81  5322.4 1731.68  5484.5 1735.97
#Mann=3,-1,0
  4498.5    0.05       0  5019.2    0.03       0  5023.2    0.05       0
Bank Sta=5019.2,5023.2
Exp/Cntr=0.3,0.1

Type RM Length L Ch R = 1,10523,352,352,352
BEGIN DESCRIPTION:
Deadman 38 22.0
END DESCRIPTION:
XS GIS Cut Line= 3
      1635985.90      6913254.68      1636463.35      6913699.57
      1636905.00      6913938.00
#Sta/Elev= 30
  4360.9 1726.52  4440.6 1725.85  4447.5 1725.50  4511.0 1725.34  4539.3 1724.84
  4546.7 1725.05  4666.8 1724.48  4702.0 1724.00  4716.2 1724.28  4744.5 1723.58
  4856.1 1723.09  4866.8 1723.18  4949.7 1723.46  4957.1 1722.89  4971.2 1722.95
  5009.0 1721.00  5009.3 1720.50  5013.1 1720.50  5013.4 1721.00  5017.1 1721.00
  5020.9 1721.81  5037.1 1722.14  5049.5 1723.47  5059.0 1723.83  5064.7 1724.94
  5080.9 1725.07  5130.3 1726.80  5354.1 1732.34  5381.6 1733.64  5515.4 1737.03
#Mann=5,-1,0
  4360.9    0.05       0  4856.1    0.12       0  4866.8    0.05       0
  5009.0    0.05       0  5013.4    0.05       0
Bank Sta=5009,5013.4
Exp/Cntr=0.3,0.1

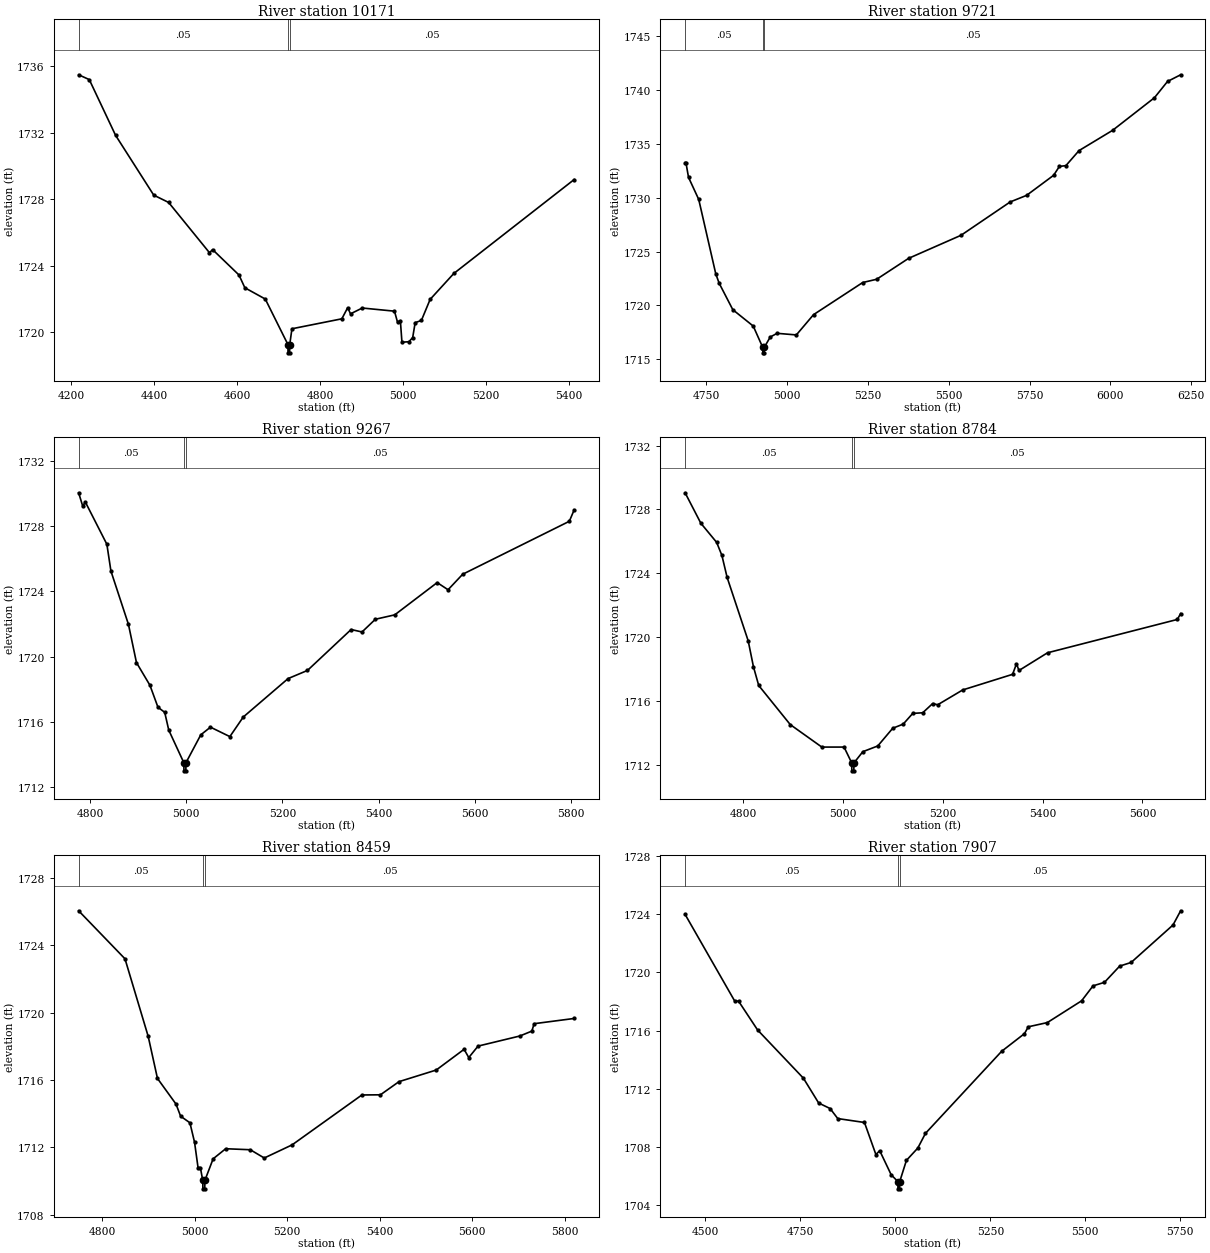
Type RM Length L Ch R = 1,10171,450,450,450
BEGIN DESCRIPTION:
Deadman 38 21.0
END DESCRIPTION:
XS GIS Cut Line= 3
      1635632.16      6913254.67      1636155.00      6913838.00
      1636498.11      6914066.35
#Sta/Elev= 30
  4217.7 1735.49  4243.4 1735.20  4306.9 1731.84  4398.9 1728.24  4434.8 1727.80
  4533.4 1724.77  4540.9 1724.96  4604.5 1723.43  4618.7 1722.66  4668.0 1721.98
  4722.6 1719.24  4722.9 1718.74  4726.7 1718.74  4727.0 1719.24  4732.3 1720.19
  4852.7 1720.79  4866.8 1721.46  4873.6 1721.09  4902.0 1721.44  4979.7 1721.25
  4987.2 1720.57  4993.9 1720.68  4997.7 1719.38  5014.6 1719.41  5023.6 1719.66
  5029.6 1720.56  5044.6 1720.69  5065.7 1721.96  5122.8 1723.52  5413.2 1729.18
#Mann=3,-1,0
  4217.7    0.05       0  4722.6    0.05       0  4727.0    0.05       0
Bank Sta=4722.6,4727
Exp/Cntr=0.3,0.1

Type RM Length L Ch R = 1,9721,454,454,454
BEGIN DESCRIPTION:
Deadman 38 20.0
END DESCRIPTION:
XS GIS Cut Line= 3
      1635504.99      6913938.00      1635805.00      6914038.00
      1637005.01      6914238.00
#Sta/Elev= 30
  4684.5 1733.24  4687.1 1733.24  4695.1 1731.88  4726.7 1729.83  4779.4 1722.93
  4789.9 1722.06  4832.1 1719.61  4895.3 1718.09  4924.7 1716.11  4925.0 1715.61
  4928.9 1715.61  4929.2 1716.11  4948.0 1717.08  4969.1 1717.42  5028.6 1717.27
  5081.8 1719.15  5233.9 1722.13  5277.0 1722.43  5375.8 1724.37  5538.1 1726.51
  5690.1 1729.60  5740.8 1730.21  5824.4 1732.07  5842.2 1732.89  5862.5 1732.97
  5903.0 1734.36  6006.9 1736.24  6136.2 1739.26  6176.7 1740.77  6217.3 1741.39
#Mann=3,-1,0
  4684.5    0.05       0  4924.7    0.03       0  4929.2    0.05       0
Bank Sta=4924.7,4929.2
Exp/Cntr=0.3,0.1

Type RM Length L Ch R = 1,9267,483,483,483
BEGIN DESCRIPTION:
Deadman 38 19.0
END DESCRIPTION:
XS GIS Cut Line= 3
      1635454.97      6914337.98      1635655.00      6914438.00
      1636455.03      6914338.00
#Sta/Elev= 30
  4776.6 1730.05  4785.0 1729.24  4790.6 1729.48  4835.3 1726.89  4843.7 1725.25
  4880.1 1721.98  4896.8 1719.63  4924.8 1718.24  4941.5 1716.89  4955.5 1716.58
  4963.9 1715.49  4995.2 1713.49  4995.5 1712.99  4999.4 1712.99  4999.7 1713.49
  5030.5 1715.20  5050.6 1715.67  5090.9 1715.09  5118.7 1716.29  5211.9 1718.65
  5252.2 1719.15  5342.9 1721.66  5365.6 1721.51  5393.3 1722.29  5433.6 1722.56
  5521.8 1724.54  5544.4 1724.10  5574.7 1725.05  5796.4 1728.30  5806.5 1729.00
#Mann=3,-1,0
  4776.6    0.05       0  4995.2    0.03       0  4999.7    0.05       0
Bank Sta=4995.2,4999.7
Exp/Cntr=0.3,0.1

Type RM Length L Ch R = 1,8784,325,325,325
BEGIN DESCRIPTION:
Deadman 38 18.0
END DESCRIPTION:
XS GIS Cut Line= 3
      1635254.99      6914788.00      1635555.00      6914888.00
      1636231.64      6914916.95
#Sta/Elev= 30
  4683.1 1729.04  4714.7 1727.13  4746.4 1725.93  4756.9 1725.11  4767.4 1723.73
  4809.6 1719.76  4820.1 1718.14  4830.7 1716.96  4893.9 1714.51  4957.2 1713.10
  5001.8 1713.10  5017.1 1712.11  5017.4 1711.61  5021.3 1711.61  5021.7 1712.11
  5039.4 1712.81  5069.4 1713.17  5099.4 1714.28  5120.4 1714.54  5139.5 1715.21
  5159.5 1715.25  5179.5 1715.83  5189.5 1715.75  5239.6 1716.68  5339.7 1717.66
  5347.5 1718.32  5352.5 1717.90  5409.7 1719.01  5670.0 1721.10  5676.6 1721.47
#Mann=3,-1,0
  4683.1    0.05       0  5017.1    0.03       0  5021.7    0.05       0
Bank Sta=5017.1,5021.7
Exp/Cntr=0.3,0.1

Type RM Length L Ch R = 1,8459,552,552,552
BEGIN DESCRIPTION:
Deadman 38 17.0
END DESCRIPTION:
XS GIS Cut Line= 3
      1635155.00      6915138.00      1635415.04      6915159.29
      1636221.87      6915073.38
#Sta/Elev= 30
  4748.6 1726.04  4848.9 1723.19  4899.1 1718.59  4919.2 1716.09  4959.3 1714.57
  4969.3 1713.85  4989.4 1713.46  4999.4 1712.31  5007.0 1710.80  5012.0 1710.80
  5017.2 1710.04  5017.5 1709.54  5021.5 1709.54  5021.8 1710.04  5039.6 1711.32
  5066.8 1711.92  5120.1 1711.86  5150.3 1711.37  5210.6 1712.15  5361.5 1715.11
  5401.7 1715.12  5441.8 1715.90  5522.4 1716.59  5582.7 1717.82  5592.8 1717.33
  5612.9 1718.01  5703.4 1718.61  5729.3 1718.90  5734.3 1719.34  5820.9 1719.65
#Mann=3,-1,0
  4748.6    0.05       0  5017.2    0.03       0  5021.8    0.05       0
Bank Sta=5017.2,5021.8
Exp/Cntr=0.3,0.1

Type RM Length L Ch R = 1,7907,481,481,481
BEGIN DESCRIPTION:
Deadman 38 16.0
END DESCRIPTION:
XS GIS Cut Line= 3
      1635054.96      6915688.00      1635605.00      6915638.00
      1636355.02      6915688.00
#Sta/Elev= 30
  4446.8 1724.00  4577.4 1718.03  4587.4 1718.03  4637.6 1716.04  4758.1 1712.72
  4798.3 1711.01  4828.4 1710.63  4848.5 1709.94  4918.8 1709.67  4948.9 1707.46
  4958.9 1707.73  4989.1 1706.07  5006.7 1705.60  5007.0 1705.10  5011.2 1705.10
  5011.6 1705.60  5029.2 1707.06  5059.2 1707.91  5079.3 1708.92  5279.7 1714.57
  5339.9 1715.79  5349.9 1716.26  5400.0 1716.55  5490.2 1718.05  5520.3 1719.08
  5550.3 1719.32  5590.4 1720.44  5620.5 1720.69  5730.7 1723.27  5750.8 1724.25
#Mann=3,-1,0
  4446.8    0.05       0  5006.7    0.03       0  5011.6    0.05       0
Bank Sta=5006.7,5011.6
Exp/Cntr=0.3,0.1

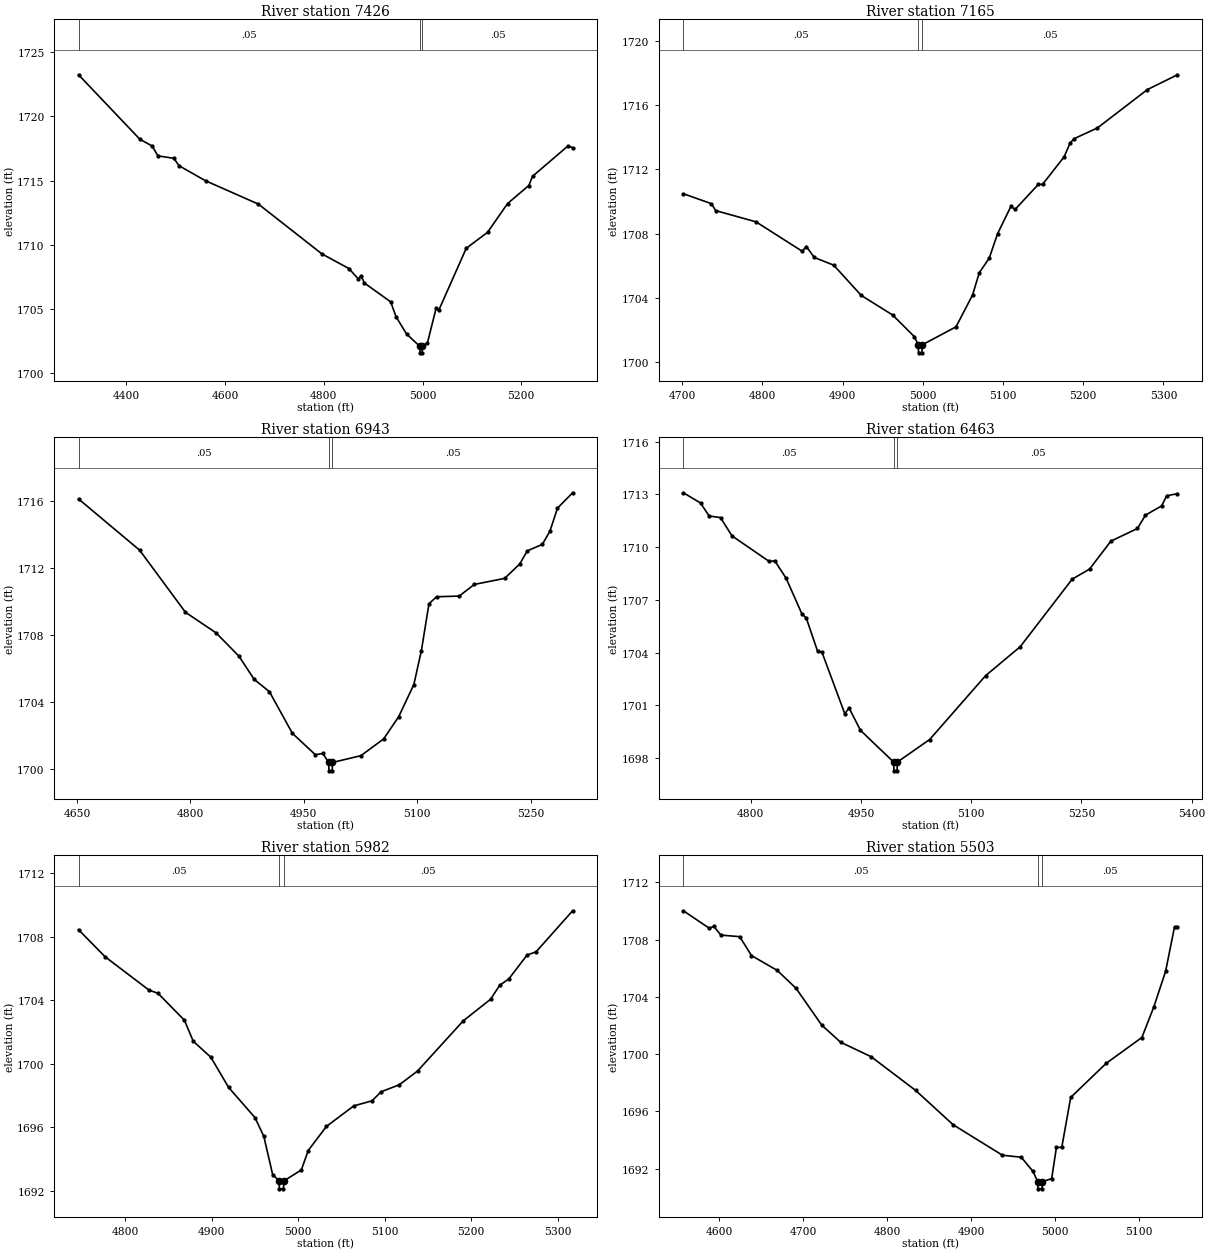
Type RM Length L Ch R = 1,7426,261,261,261
BEGIN DESCRIPTION:
Deadman 38 15.0
END DESCRIPTION:
XS GIS Cut Line= 3
      1635054.96      6915837.98      1635705.00      6916088.00
      1636005.00      6916138.00
#Sta/Elev= 30
  4303.4 1723.25  4427.7 1718.22  4452.4 1717.70  4464.2 1716.93  4496.3 1716.74
  4507.0 1716.16  4560.6 1714.99  4667.7 1713.17  4796.3 1709.29  4850.9 1708.15
  4870.2 1707.33  4875.6 1707.60  4882.0 1707.03  4935.6 1705.55  4946.3 1704.40
  4967.7 1703.05  4994.7 1702.08  4995.1 1701.58  4999.3 1701.58  4999.7 1702.08
  5010.0 1702.36  5027.7 1705.08  5032.8 1704.89  5088.6 1709.73  5131.7 1710.97
  5172.2 1713.21  5215.3 1714.62  5222.9 1715.34  5293.9 1717.68  5304.0 1717.58
#Mann=3,-1,0
  4303.4    0.05       0  4994.7    0.03       0  4999.7    0.05       0
Bank Sta=4994.7,4999.7
Exp/Cntr=0.3,0.1

Type RM Length L Ch R = 1,7165,222,222,222
BEGIN DESCRIPTION:
Mapping XS e66692a0
END DESCRIPTION:
XS GIS Cut Line= 2
      1635367.79      6916253.21      1635961.03      6916418.37
#Sta/Elev= 30
  4701.6 1710.48  4736.6 1709.86  4741.8 1709.43  4792.1 1708.73  4849.6 1706.90
  4854.8 1707.19  4864.8 1706.51  4889.0 1706.03  4923.2 1704.15  4962.6 1702.92
  4989.4 1701.58  4994.3 1701.07  4994.7 1700.57  4998.9 1700.57  4999.3 1701.07
  5041.4 1702.19  5062.0 1704.17  5070.4 1705.56  5082.8 1706.47  5093.2 1707.99
  5109.8 1709.69  5115.0 1709.50  5144.0 1711.06  5149.2 1711.06  5176.2 1712.78
  5183.5 1713.63  5188.6 1713.91  5217.7 1714.58  5280.0 1716.97  5317.4 1717.89
#Mann=3,-1,0
  4701.6    0.05       0  4994.3    0.03       0  4999.3    0.05       0
Bank Sta=4994.3,4999.3
Exp/Cntr=0.3,0.1

Type RM Length L Ch R = 1,6943,480,480,480
BEGIN DESCRIPTION:
Deadman 38 14.0
END DESCRIPTION:
XS GIS Cut Line= 3
      1635255.04      6916587.99      1635605.00      6916538.00
      1635904.99      6916538.00
#Sta/Elev= 30
  4652.2 1716.15  4733.0 1713.08  4793.6 1709.36  4834.0 1708.13  4864.3 1706.73
  4884.5 1705.34  4904.7 1704.60  4935.0 1702.11  4965.3 1700.83  4975.4 1700.90
  4983.0 1700.36  4983.4 1699.86  4987.7 1699.86  4988.0 1700.36  5025.7 1700.77
  5055.7 1701.77  5075.7 1703.11  5095.7 1705.03  5105.7 1707.07  5115.7 1709.87
  5125.7 1710.29  5155.7 1710.33  5175.7 1711.03  5215.7 1711.39  5235.7 1712.25
  5245.7 1713.04  5265.7 1713.43  5275.7 1714.22  5285.7 1715.60  5305.7 1716.52
#Mann=3,-1,0
  4652.2    0.05       0  4983.0    0.03       0  4988.0    0.05       0
Bank Sta=4983,4988
Exp/Cntr=0.3,0.1

Type RM Length L Ch R = 1,6463,481,481,481
BEGIN DESCRIPTION:
Deadman 38 13.0
END DESCRIPTION:
XS GIS Cut Line= 3
      1635254.99      6916838.00      1635505.00      6916988.00
      1635854.96      6916838.02
#Sta/Elev= 30
  4708.3 1713.09  4731.6 1712.51  4743.3 1711.77  4758.8 1711.68  4774.4 1710.64
  4824.9 1709.19  4832.7 1709.22  4848.2 1708.22  4869.6 1706.20  4875.5 1705.97
  4891.0 1704.07  4896.8 1704.03  4927.9 1700.53  4933.8 1700.85  4949.3 1699.58
  4994.4 1697.78  4994.8 1697.28  4999.1 1697.28  4999.5 1697.78  5043.4 1699.06
  5119.5 1702.69  5166.7 1704.34  5237.4 1708.18  5261.0 1708.75  5290.0 1710.34
  5326.2 1711.06  5337.1 1711.82  5358.9 1712.34  5366.1 1712.92  5380.6 1713.04
#Mann=3,-1,0
  4708.3    0.05       0  4994.4    0.03       0  4999.5    0.05       0
Bank Sta=4994.4,4999.5
Exp/Cntr=0.3,0.1

Type RM Length L Ch R = 1,5982,479,479,479
BEGIN DESCRIPTION:
Deadman 38 12.0
END DESCRIPTION:
XS GIS Cut Line= 3
      1635355.00      6917388.00      1635605.00      6917438.00
      1635905.02      6917538.01
#Sta/Elev= 30
  4746.1 1708.44  4776.7 1706.74  4827.7 1704.63  4837.9 1704.44  4868.5 1702.74
  4878.7 1701.42  4899.1 1700.41  4919.5 1698.52  4950.1 1696.61  4960.3 1695.43
  4970.5 1693.03  4977.9 1692.63  4978.3 1692.13  4983.0 1692.13  4983.5 1692.63
  5003.7 1693.32  5011.6 1694.54  5032.7 1696.06  5064.3 1697.35  5085.4 1697.67
  5095.9 1698.24  5117.0 1698.68  5138.1 1699.55  5190.8 1702.70  5222.4 1704.06
  5233.0 1704.94  5243.5 1705.34  5264.6 1706.84  5275.1 1707.05  5317.3 1709.63
#Mann=3,-1,0
  4746.1    0.05       0  4977.9    0.03       0  4983.5    0.05       0
Bank Sta=4977.9,4983.5
Exp/Cntr=0.3,0.1

Type RM Length L Ch R = 1,5503,461,461,461
BEGIN DESCRIPTION:
Deadman 38 11.0
END DESCRIPTION:
XS GIS Cut Line= 3
      1635254.99      6917688.00      1635655.00      6917888.00
      1635754.97      6917987.97
#Sta/Elev= 30
  4557.2 1710.02  4588.0 1708.80  4593.5 1708.93  4601.9 1708.32  4624.3 1708.21
  4638.3 1706.89  4669.0 1705.85  4691.4 1704.60  4722.1 1702.02  4744.5 1700.83
  4780.8 1699.82  4833.9 1697.46  4878.6 1695.06  4937.3 1692.93  4959.7 1692.79
  4973.7 1691.80  4979.3 1691.08  4979.7 1690.58  4984.4 1690.58  4984.9 1691.08
  4996.0 1691.30  5001.6 1693.48  5008.0 1693.48  5018.6 1696.97  5061.0 1699.36
  5103.4 1701.16  5117.6 1703.29  5131.7 1705.79  5142.3 1708.89  5145.8 1708.89
#Mann=3,-1,0
  4557.2    0.05       0  4979.3    0.05       0  4984.9    0.05       0
Bank Sta=4979.3,4984.9
Exp/Cntr=0.3,0.1

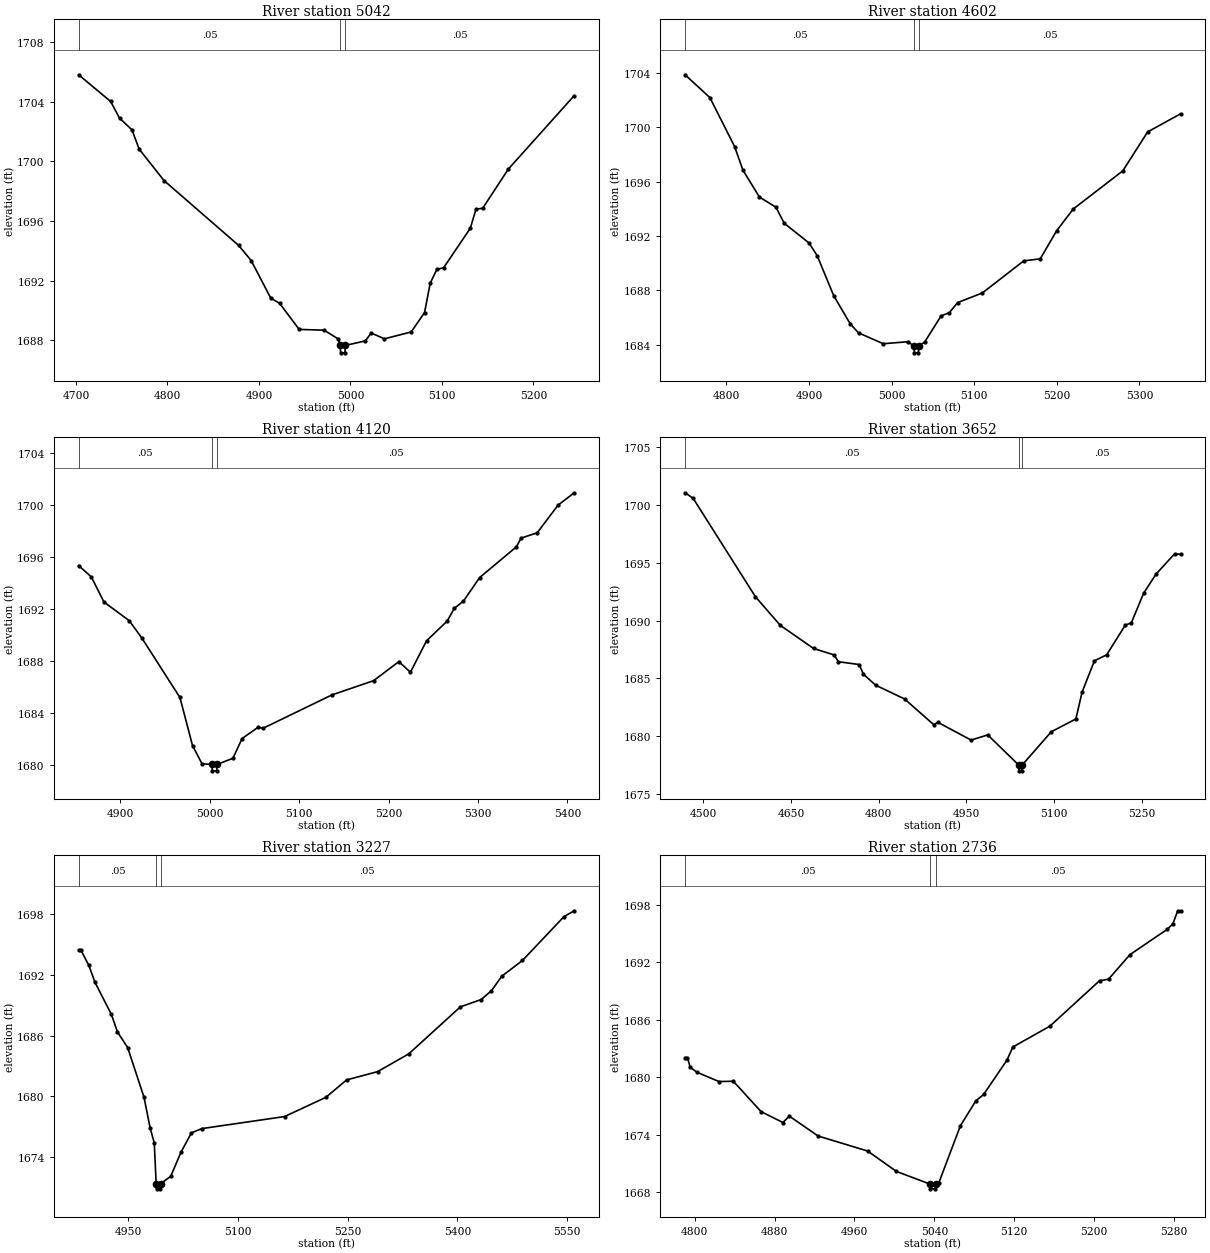
Type RM Length L Ch R = 1,5042,440,440,440
BEGIN DESCRIPTION:
Deadman 38 10.0
END DESCRIPTION:
XS GIS Cut Line= 3
      1635155.01      6917888.02      1635305.00      6918138.00
      1635504.98      6918287.99
#Sta/Elev= 30
  4703.0 1705.80  4738.0 1704.01  4747.7 1702.89  4761.3 1702.11  4769.1 1700.82
  4796.3 1698.71  4877.9 1694.36  4891.5 1693.35  4912.9 1690.83  4922.6 1690.48
  4944.0 1688.73  4971.2 1688.68  4986.7 1688.09  4988.8 1687.66  4989.3 1687.16
  4994.0 1687.16  4994.5 1687.66  5016.4 1687.96  5022.6 1688.49  5037.2 1688.10
  5066.4 1688.56  5081.0 1689.86  5087.2 1691.83  5094.5 1692.76  5101.8 1692.86
  5131.0 1695.51  5137.2 1696.79  5144.5 1696.85  5172.6 1699.48  5244.5 1704.40
#Mann=3,-1,0
  4703.0    0.05       0  4988.8    0.03       0  4994.5    0.05       0
Bank Sta=4988.8,4994.5
Exp/Cntr=0.3,0.1

Type RM Length L Ch R = 1,4602,482,482,482
BEGIN DESCRIPTION:
Deadman 38 9.0
END DESCRIPTION:
XS GIS Cut Line= 3
      1634755.03      6918388.00      1635005.00      6918388.00
      1635355.03      6918388.00
#Sta/Elev= 30
  4749.9 1703.86  4779.9 1702.18  4809.9 1698.57  4819.9 1696.84  4839.9 1694.86
  4859.9 1694.11  4869.9 1692.93  4899.9 1691.48  4909.9 1690.53  4929.9 1687.59
  4949.9 1685.52  4959.9 1684.86  4989.9 1684.06  5019.9 1684.21  5027.0 1683.89
  5027.5 1683.39  5032.3 1683.39  5032.8 1683.89  5039.9 1684.18  5059.9 1686.11
  5069.9 1686.35  5079.9 1687.09  5109.9 1687.80  5159.9 1690.16  5179.9 1690.31
  5199.9 1692.39  5219.9 1693.98  5279.9 1696.79  5309.9 1699.65  5349.9 1700.99
#Mann=3,-1,0
  4749.9    0.05       0  5027.0    0.05       0  5032.8    0.05       0
Bank Sta=5027,5032.8
Exp/Cntr=0.3,0.1

Type RM Length L Ch R = 1,4120,468,468,468
BEGIN DESCRIPTION:
Deadman 38 8.0
END DESCRIPTION:
XS GIS Cut Line= 3
      1634804.98      6918737.98      1634905.00      6918838.00
      1635305.04      6918938.01
#Sta/Elev= 30
  4853.7 1695.36  4867.9 1694.48  4882.0 1692.55  4910.3 1691.11  4924.4 1689.77
  4966.9 1685.20  4981.0 1681.49  4991.6 1680.09  5002.6 1680.05  5003.1 1679.55
  5007.9 1679.55  5008.4 1680.05  5026.1 1680.51  5036.4 1682.04  5054.4 1682.91
  5059.6 1682.82  5136.9 1685.40  5183.3 1686.49  5211.6 1687.96  5224.5 1687.14
  5242.5 1689.56  5265.7 1691.09  5273.5 1692.06  5283.8 1692.62  5301.8 1694.43
  5343.0 1696.80  5348.2 1697.47  5366.2 1697.88  5389.4 1700.00  5407.5 1700.96
#Mann=3,-1,0
  4853.7    0.05       0  5002.6    0.05       0  5008.4    0.05       0
Bank Sta=5002.6,5008.4
Exp/Cntr=0.3,0.1

Type RM Length L Ch R = 1,3652,425,425,425
BEGIN DESCRIPTION:
Deadman 38 7.0
END DESCRIPTION:
XS GIS Cut Line= 3
      1634455.00      6918938.00      1634855.00      6919288.00
      1635154.96      6919188.01
#Sta/Elev= 30
  4468.7 1701.06  4482.5 1700.58  4588.8 1692.08  4631.5 1689.59  4688.4 1687.59
  4723.5 1687.03  4731.1 1686.44  4766.3 1686.20  4773.8 1685.36  4794.7 1684.41
  4844.1 1683.22  4893.9 1681.00  4901.0 1681.20  4958.0 1679.66  4986.4 1680.11
  5039.4 1677.50  5039.9 1677.00  5044.8 1677.00  5045.3 1677.50  5095.1 1680.38
  5137.2 1681.49  5147.8 1683.81  5168.9 1686.52  5189.9 1687.04  5221.6 1689.60
  5232.1 1689.81  5253.2 1692.38  5274.3 1694.02  5305.9 1695.77  5316.4 1695.74
#Mann=3,-1,0
  4468.7    0.05       0  5039.4    0.03       0  5045.3    0.05       0
Bank Sta=5039.4,5045.3
Exp/Cntr=0.3,0.1

Type RM Length L Ch R = 1,3227,491,491,491
BEGIN DESCRIPTION:
Deadman 38 6.0
END DESCRIPTION:
XS GIS Cut Line= 3
      1634805.02      6919737.96      1634855.00      6919638.00
      1635254.97      6919238.03
#Sta/Elev= 30
  4882.2 1694.48  4885.0 1694.48  4896.1 1692.95  4904.5 1691.27  4926.9 1688.10
  4935.3 1686.36  4949.2 1684.82  4971.6 1679.90  4980.0 1676.85  4985.6 1675.40
  4988.2 1671.36  4988.7 1670.86  4993.7 1670.86  4994.2 1671.36  5008.1 1672.10
  5022.2 1674.49  5036.4 1676.39  5050.5 1676.81  5163.7 1678.00  5220.2 1679.90
  5248.5 1681.62  5290.9 1682.44  5333.4 1684.19  5404.1 1688.84  5432.4 1689.56
  5446.5 1690.43  5460.7 1691.87  5488.9 1693.42  5545.5 1697.74  5559.6 1698.33
#Mann=3,-1,0
  4882.2    0.05       0  4988.2    0.05       0  4994.2    0.05       0
Bank Sta=4988.2,4994.2
Exp/Cntr=0.3,0.1

Type RM Length L Ch R = 1,2736,166,166,166
BEGIN DESCRIPTION:
Deadman 38 5.0
END DESCRIPTION:
XS GIS Cut Line= 3
      1635177.02      6919847.27      1635315.44      6919675.08
      1635454.98      6919438.03
#Sta/Elev= 30
  4790.5 1682.04  4792.9 1682.04  4795.6 1681.04  4802.4 1680.52  4824.4 1679.55
  4838.8 1679.58  4866.5 1676.41  4888.4 1675.27  4894.8 1675.94  4923.6 1673.86
  4973.2 1672.29  5002.0 1670.16  5035.5 1668.84  5036.0 1668.34  5041.1 1668.34
  5041.6 1668.84  5044.4 1668.95  5066.1 1674.94  5081.5 1677.53  5089.3 1678.20
  5112.5 1681.76  5118.6 1683.16  5155.7 1685.34  5205.3 1690.08  5214.3 1690.24
  5235.8 1692.81  5272.9 1695.44  5278.7 1696.02  5283.6 1697.39  5286.5 1697.39
#Mann=3,-1,0
  4790.5    0.05       0  5035.5    0.05       0  5041.6    0.05       0
Bank Sta=5035.5,5041.6
Exp/Cntr=0.3,0.1

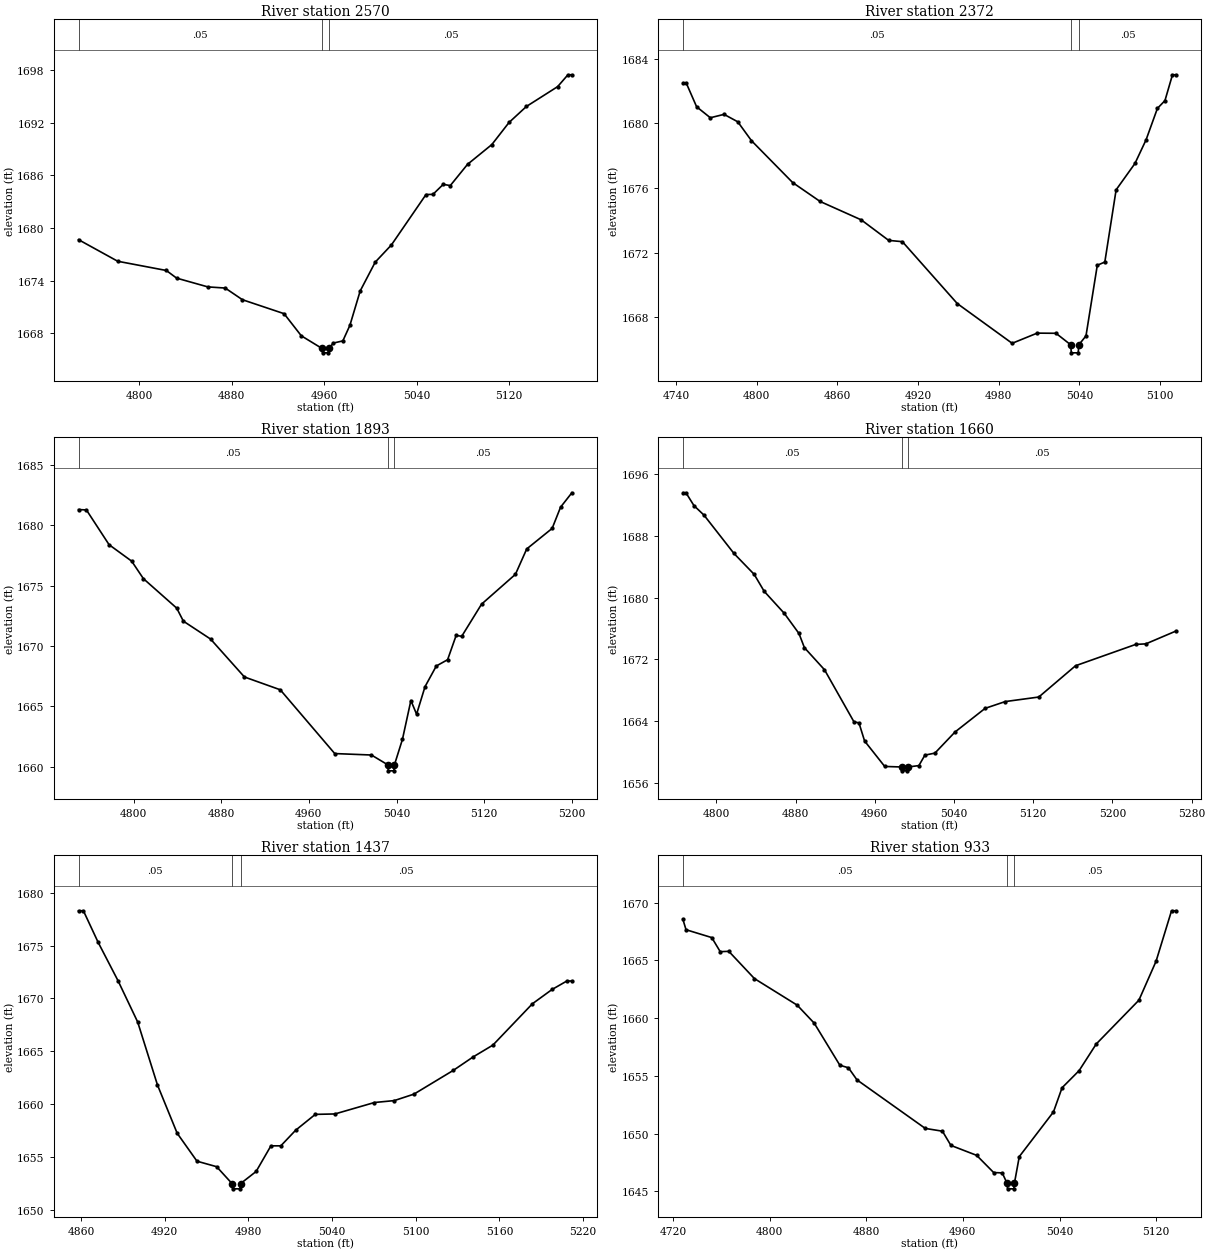
Type RM Length L Ch R = 1,2570,198,198,198
BEGIN DESCRIPTION:
Mapping XS 19f24be8
END DESCRIPTION:
XS GIS Cut Line= 2
      1635242.87      6919882.71      1635595.65      6919643.03
#Sta/Elev= 30
  4747.7 1678.67  4781.6 1676.21  4823.6 1675.16  4832.5 1674.29  4859.5 1673.29
  4874.5 1673.16  4889.4 1671.83  4925.4 1670.24  4940.3 1667.72  4958.2 1666.28
  4958.7 1665.78  4963.8 1665.78  4964.3 1666.28  4967.9 1666.89  4976.2 1667.14
  4982.3 1668.91  4991.2 1672.83  5004.2 1676.11  5018.2 1678.07  5048.1 1683.81
  5054.1 1683.83  5063.0 1684.97  5069.1 1684.83  5084.0 1687.25  5105.0 1689.50
  5119.9 1692.02  5134.9 1693.84  5161.9 1696.10  5170.8 1697.45  5174.2 1697.45
#Mann=3,-1,0
  4747.7    0.05       0  4958.2    0.05       0  4964.3    0.05       0
Bank Sta=4958.2,4964.3
Exp/Cntr=0.3,0.1

Type RM Length L Ch R = 1,2372,479,479,479
BEGIN DESCRIPTION:
Deadman 38 4.0
END DESCRIPTION:
XS GIS Cut Line= 3
      1635204.96      6919988.01      1635455.00      6919938.00
      1635555.00      6919888.00
#Sta/Elev= 30
  4745.2 1682.47  4747.8 1682.47  4755.4 1681.02  4765.6 1680.34  4775.8 1680.55
  4786.0 1680.09  4796.2 1678.92  4826.8 1676.33  4847.2 1675.16  4877.8 1674.02
  4898.2 1672.75  4908.4 1672.67  4949.2 1668.84  4990.0 1666.38  5008.6 1667.01
  5022.6 1667.00  5033.5 1666.29  5034.0 1665.79  5039.1 1665.79  5039.6 1666.29
  5044.9 1666.84  5053.3 1671.21  5058.9 1671.41  5067.3 1675.88  5081.3 1677.51
  5089.6 1678.98  5098.0 1680.92  5103.6 1681.40  5109.2 1683.00  5112.0 1683.00
#Mann=3,-1,0
  4745.2    0.05       0  5033.5    0.05       0  5039.6    0.05       0
Bank Sta=5033.5,5039.6
Exp/Cntr=0.3,0.1

Type RM Length L Ch R = 1,1893,233,233,233
BEGIN DESCRIPTION:
Deadman 38 3.0
END DESCRIPTION:
XS GIS Cut Line= 3
      1635117.91      6920330.08      1635355.00      6920388.00
      1635554.99      6920338.00
#Sta/Elev= 30
  4749.8 1681.30  4757.0 1681.27  4777.7 1678.39  4798.3 1677.03  4809.0 1675.58
  4839.4 1673.14  4845.5 1672.06  4870.3 1670.58  4901.2 1667.44  4933.9 1666.38
  4983.6 1661.10  5017.1 1660.98  5032.0 1660.17  5032.5 1659.67  5037.6 1659.67
  5038.1 1660.17  5045.4 1662.28  5053.1 1665.49  5058.3 1664.36  5066.0 1666.64
  5076.3 1668.35  5086.6 1668.87  5094.4 1670.88  5099.5 1670.81  5117.6 1673.47
  5148.5 1675.94  5158.8 1678.04  5182.0 1679.74  5189.7 1681.50  5200.0 1682.69
#Mann=3,-1,0
  4749.8    0.05       0  5032.0    0.05       0  5038.1    0.05       0
Bank Sta=5032,5038.1
Exp/Cntr=0.3,0.1

Type RM Length L Ch R = 1,1660,223,223,223
BEGIN DESCRIPTION:
Mapping XS 34c3df3f
END DESCRIPTION:
XS GIS Cut Line= 2
      1635074.00      6920642.40      1635565.28      6920559.67
#Sta/Elev= 30
  4766.2 1693.62  4769.3 1693.62  4777.4 1691.95  4787.5 1690.72  4817.8 1685.74
  4838.2 1683.03  4848.3 1680.83  4868.6 1677.97  4883.4 1675.36  4888.9 1673.52
  4909.2 1670.65  4938.9 1663.90  4944.0 1663.75  4949.7 1661.40  4970.0 1658.10
  4987.2 1658.03  4987.7 1657.53  4992.9 1657.53  4993.4 1658.03  5004.5 1658.21
  5010.6 1659.57  5020.7 1659.83  5041.0 1662.57  5071.4 1665.64  5091.7 1666.52
  5125.6 1667.11  5162.7 1671.17  5223.5 1673.94  5233.7 1674.01  5264.4 1675.69
#Mann=3,-1,0
  4766.2    0.05       0  4987.2    0.05       0  4993.4    0.05       0
Bank Sta=4987.2,4993.4
Exp/Cntr=0.3,0.1

Type RM Length L Ch R = 1,1437,504,504,504
BEGIN DESCRIPTION:
Deadman 38 2.0
END DESCRIPTION:
XS GIS Cut Line= 3
      1635305.00      6920888.00      1635405.00      6920788.00
      1635555.03      6920637.97
#Sta/Elev= 29
  4858.3 1678.28  4861.8 1678.28  4872.4 1675.29  4886.6 1671.68  4900.7 1667.78
  4914.9 1661.83  4929.0 1657.28  4943.2 1654.64  4957.3 1654.12  4968.3 1652.53
  4968.8 1652.03  4974.0 1652.03  4974.5 1652.53  4985.6 1653.67  4996.2 1656.09
  5003.3 1656.09  5013.9 1657.56  5028.0 1659.06  5042.1 1659.10  5070.4 1660.18
  5084.6 1660.36  5098.7 1660.97  5127.0 1663.22  5141.1 1664.48  5155.3 1665.60
  5183.6 1669.50  5197.7 1670.85  5208.3 1671.65  5211.9 1671.65
#Mann=3,-1,0
  4858.3    0.05       0  4968.3    0.03       0  4974.5    0.05       0
Bank Sta=4968.3,4974.5
Exp/Cntr=0.3,0.1

Type RM Length L Ch R = 1,933,274,274,274
BEGIN DESCRIPTION:
Mapping XS 960b6835
END DESCRIPTION:
XS GIS Cut Line= 2
      1635639.53      6921206.27      1635928.24      6920917.56
#Sta/Elev= 30
  4728.3 1668.55  4730.9 1667.65  4752.2 1666.97  4759.2 1665.75  4766.3 1665.78
  4787.5 1663.42  4822.9 1661.12  4837.0 1659.56  4858.2 1655.92  4865.3 1655.70
  4872.4 1654.65  4928.9 1650.45  4943.1 1650.21  4950.1 1648.98  4971.4 1648.12
  4985.5 1646.63  4992.6 1646.60  4996.5 1645.72  4997.0 1645.22  5002.2 1645.22
  5002.7 1645.72  5006.7 1648.01  5035.0 1651.88  5042.1 1653.97  5056.2 1655.45
  5070.4 1657.76  5105.7 1661.55  5119.9 1664.92  5132.7 1669.29  5136.6 1669.29
#Mann=3,-1,0
  4728.3    0.05       0  4996.5    0.05       0  5002.7    0.05       0
Bank Sta=4996.5,5002.7
Exp/Cntr=0.3,0.1