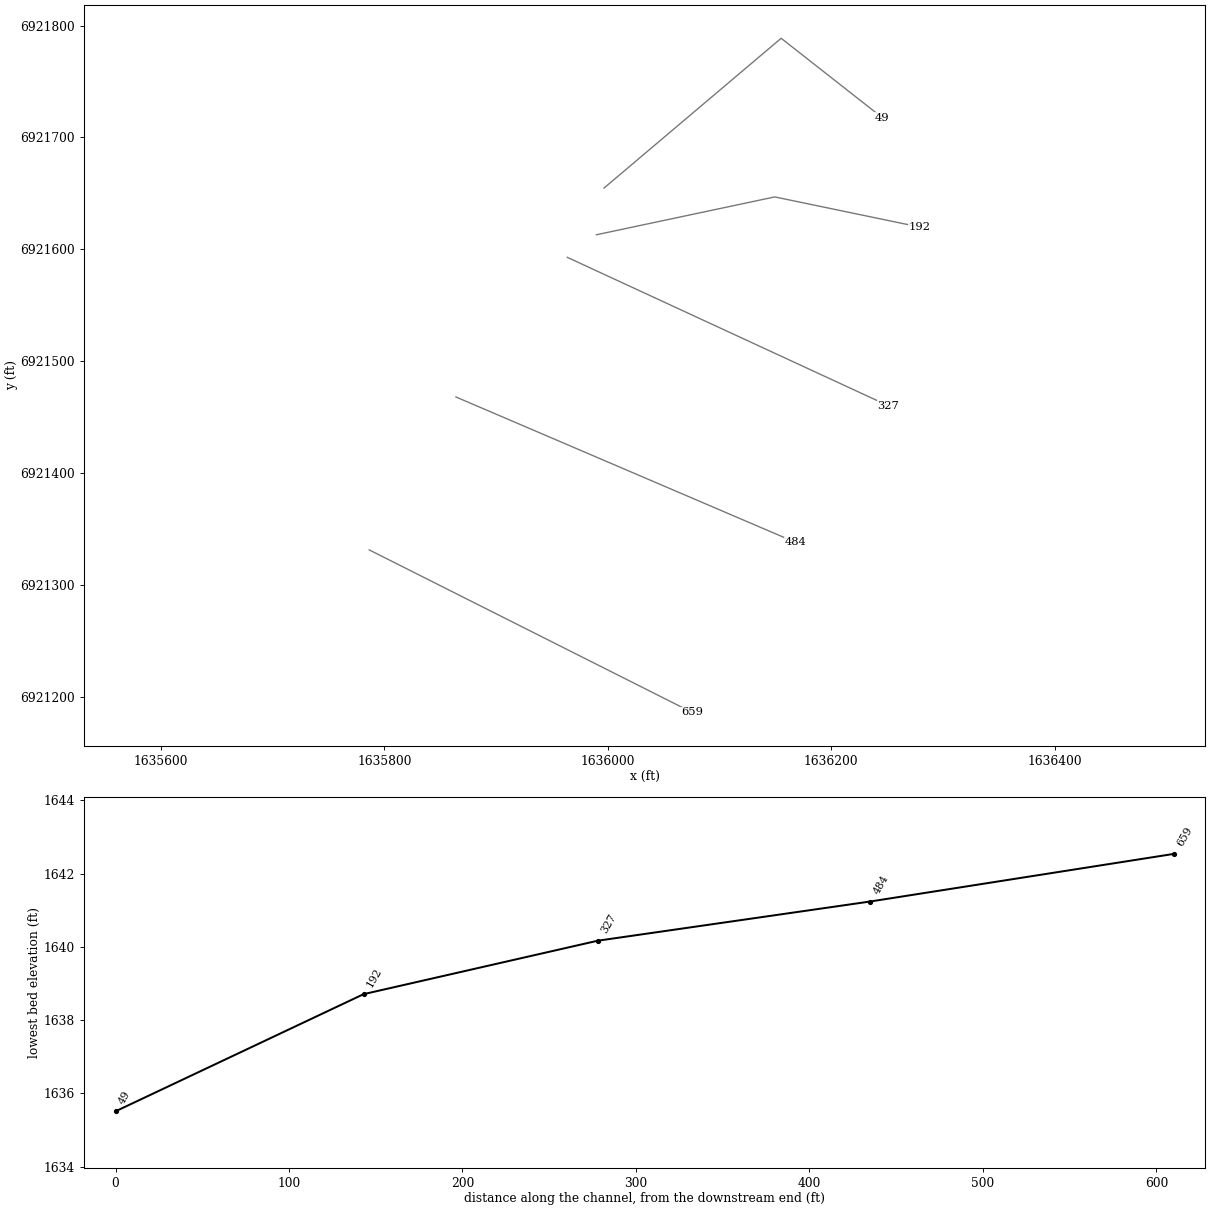
HEC-RAS study Deadman 38.prj: Deadman 38 Base Level Engineering

--- Deadman 38.g01 (geometry) --- (continued)

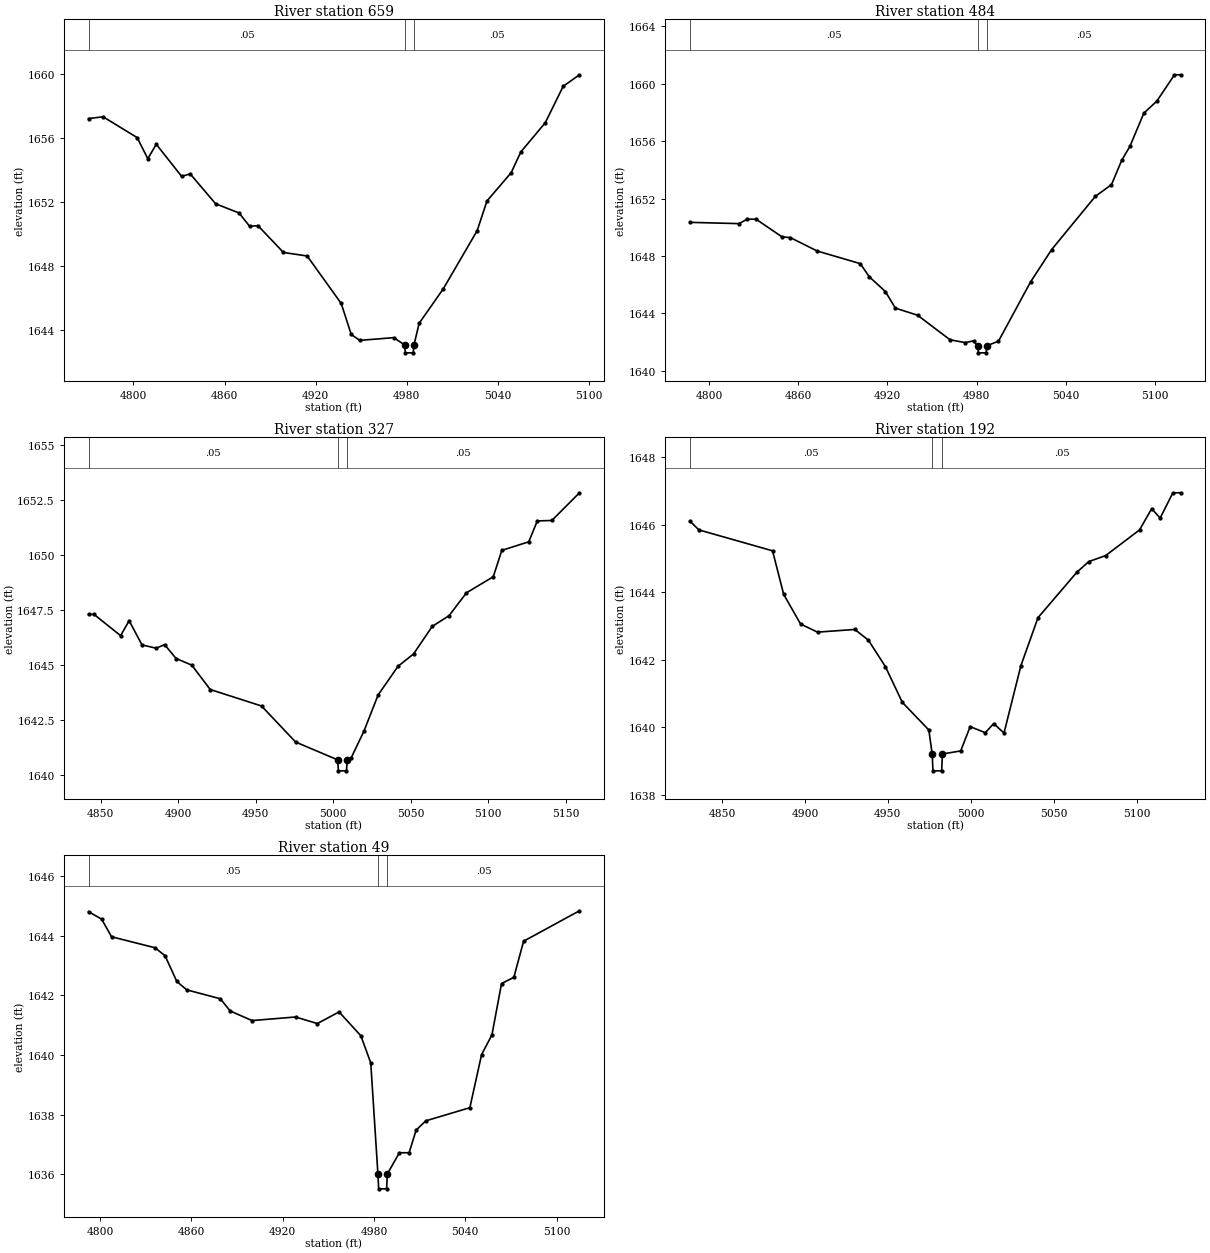
Type RM Length L Ch R = 1,659,175,175,175
BEGIN DESCRIPTION:
Mapping XS 11d51219
END DESCRIPTION:
XS GIS Cut Line= 2
      1635786.44      6921331.16      1636075.09      6921185.99
#Sta/Elev= 30
  4770.5 1657.20  4780.1 1657.31  4802.5 1656.01  4809.5 1654.69  4815.1 1655.59
  4831.8 1653.58  4837.4 1653.74  4854.1 1651.87  4869.6 1651.29  4876.5 1650.46
  4882.0 1650.50  4898.8 1648.82  4914.4 1648.60  4936.8 1645.63  4943.4 1643.69
  4949.0 1643.32  4971.3 1643.49  4978.5 1643.04  4979.0 1642.54  4984.2 1642.54
  4984.7 1643.04  4988.1 1644.39  5004.0 1646.55  5026.3 1650.19  5032.7 1652.04
  5048.7 1653.82  5055.0 1655.11  5071.1 1656.94  5082.9 1659.22  5093.6 1659.94
#Mann=3,-1,0
  4770.5    0.05       0  4978.5    0.05       0  4984.7    0.05       0
Bank Sta=4978.5,4984.7
Exp/Cntr=0.3,0.1

Type RM Length L Ch R = 1,484,157,157,157
BEGIN DESCRIPTION:
Mapping XS 2019eafd
END DESCRIPTION:
XS GIS Cut Line= 2
      1635864.05      6921467.91      1636167.92      6921337.93
#Sta/Elev= 30
  4787.0 1650.34  4820.1 1650.25  4825.5 1650.56  4831.5 1650.56  4849.1 1649.32
  4854.5 1649.28  4872.7 1648.34  4901.7 1647.46  4907.7 1646.55  4918.6 1645.51
  4925.3 1644.36  4940.3 1643.86  4962.1 1642.15  4972.5 1641.95  4977.9 1642.08
  4980.7 1641.74  4981.2 1641.24  4986.4 1641.24  4986.9 1641.74  4994.7 1642.05
  5016.4 1646.20  5030.5 1648.44  5059.9 1652.15  5070.8 1652.97  5077.7 1654.67
  5083.2 1655.64  5092.6 1657.96  5101.3 1658.79  5113.2 1660.63  5117.5 1660.63
#Mann=3,-1,0
  4787.0    0.05       0  4980.7    0.05       0  4986.9    0.05       0
Bank Sta=4980.7,4986.9
Exp/Cntr=0.3,0.1

Type RM Length L Ch R = 1,327,135,135,135
BEGIN DESCRIPTION:
Mapping XS f3daf077
END DESCRIPTION:
XS GIS Cut Line= 2
      1635963.70      6921592.82      1636251.20      6921460.00
#Sta/Elev= 30
  4842.2 1647.29  4845.7 1647.29  4862.9 1646.32  4868.4 1647.00  4876.7 1645.90
  4885.8 1645.75  4891.3 1645.91  4898.7 1645.28  4908.8 1644.98  4920.7 1643.87
  4953.8 1643.12  4975.8 1641.48  5002.9 1640.67  5003.4 1640.17  5008.6 1640.17
  5009.1 1640.67  5011.5 1640.74  5019.9 1641.98  5029.0 1643.62  5041.9 1644.93
  5051.9 1645.49  5063.9 1646.74  5074.8 1647.23  5086.0 1648.27  5103.3 1649.00
  5108.8 1650.20  5126.2 1650.59  5131.7 1651.54  5141.1 1651.56  5158.9 1652.82
#Mann=3,-1,0
  4842.2    0.05       0  5002.9    0.03       0  5009.1    0.05       0
Bank Sta=5002.9,5009.1
Exp/Cntr=0.3,0.1

Type RM Length L Ch R = 1,192,143,143,143
BEGIN DESCRIPTION:
Mapping XS e357bacf
END DESCRIPTION:
XS GIS Cut Line= 3
      1635989.76      6921613.00      1636149.39      6921646.84
      1636279.34      6921619.84
#Sta/Elev= 30
  4830.7 1646.11  4836.1 1645.85  4880.5 1645.23  4887.2 1643.94  4897.4 1643.06
  4907.6 1642.82  4930.1 1642.90  4938.3 1642.58  4948.5 1641.80  4958.7 1640.74
  4974.7 1639.92  4976.7 1639.21  4977.2 1638.71  4982.4 1638.71  4982.9 1639.21
  4993.9 1639.30  4999.6 1640.02  5008.7 1639.84  5013.8 1640.11  5020.0 1639.83
  5030.2 1641.83  5040.5 1643.25  5064.0 1644.60  5071.1 1644.91  5081.3 1645.09
  5101.7 1645.85  5109.0 1646.48  5114.1 1646.20  5121.8 1646.95  5126.6 1646.95
#Mann=3,-1,0
  4830.7    0.05       0  4976.7    0.03       0  4982.9    0.05       0
Bank Sta=4976.7,4982.9
Exp/Cntr=0.3,0.1

Type RM Length L Ch R = 1,49,0,0,0
BEGIN DESCRIPTION:
Deadman 38 1.0
END DESCRIPTION:
XS GIS Cut Line= 3
      1635996.60      6921654.80      1636155.10      6921788.72
      1636245.59      6921717.76
#Sta/Elev= 30
  4792.5 1644.80  4801.1 1644.55  4807.6 1643.96  4836.2 1643.59  4842.8 1643.32
  4850.5 1642.46  4857.0 1642.18  4879.1 1641.88  4885.6 1641.47  4899.9 1641.15
  4928.5 1641.27  4942.8 1641.05  4957.1 1641.44  4971.4 1640.64  4977.9 1639.73
  4982.6 1636.01  4983.1 1635.51  4988.3 1635.51  4988.8 1636.01  4996.7 1636.72
  5003.1 1636.72  5007.7 1637.48  5014.1 1637.79  5043.0 1638.23  5050.7 1640.01
  5057.5 1640.67  5063.8 1642.39  5071.9 1642.60  5078.3 1643.81  5115.0 1644.83
#Mann=3,-1,0
  4792.5    0.05       0  4982.6    0.05       0  4988.8    0.05       0
Bank Sta=4982.6,4988.8
Exp/Cntr=0.3,0.1

Chan Stop Cuts=-1