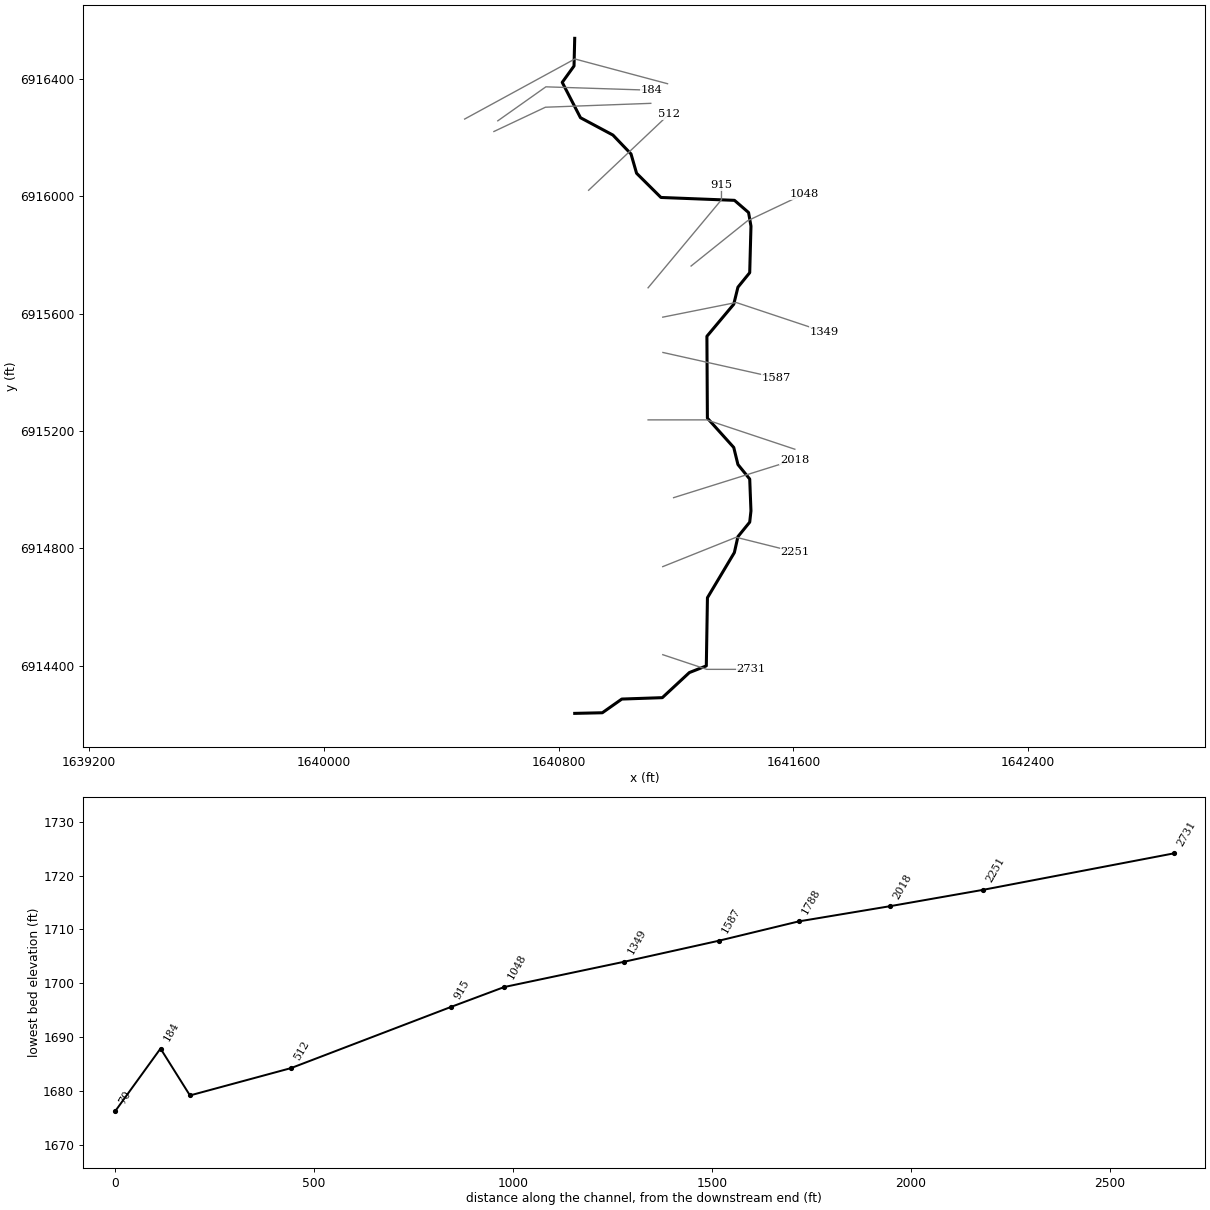
--- Deadman 39.prj (project) ---

Proj Title=Deadman 39 Base Level Engineering
Current Plan=p01
Default Exp/Contr=0.3,0.1
English Units
Geom File=g01
Flow File=f01
Plan File=p01
BEGIN DESCRIPTION:
Deadman 39
END DESCRIPTION:

--- Deadman 39.p01 (plan) ---

Plan Title=Multiple Run
Short Identifier=Multiple
Geom File=g01
Flow File=f01
Subcritical Flow
K Sum by GR= 0
Std Step Tol= 0.01
Critical Tol= 0.01
Num of Std Step Trials= 20
Max Error Tol= 0.3
Flow Tol Ratio= 0.001
Split Flow NTrial= 30
Split Flow Tol= 0.02
Split Flow Ratio= 0.02
Log Output Level= 0
Friction Slope Method= 1
Unsteady Friction Slope Method= 2
Unsteady Bridges Friction Slope Method= 1
Parabolic Critical Depth
Global Vel Dist=  1 , 1 , 1
Global Log Level= 0
CheckData=True
Encroach Param= -1, 0, 0, 0
BEGIN DESCRIPTION:
Multiple Run
END DESCRIPTION:

--- Deadman 39.f01 (steady flow) ---

Flow Title=Multiple
Number of Profiles=7
Profile Names=10-year,25-year,50-year,1pct_min,100-year,1pct_plu,500-year
River Rch & RM= Deadman 39,Reach-1,2731
     173     235     285     173     344     687     508
Boundary for River Rch & Prof#=Deadman 39,Reach-1,1
Up Type=0
Dn Type=3
Dn Slope=0.005
Boundary for River Rch & Prof#=Deadman 39,Reach-1,2
Up Type=0
Dn Type=3
Dn Slope=0.005
Boundary for River Rch & Prof#=Deadman 39,Reach-1,3
Up Type=0
Dn Type=3
Dn Slope=0.005
Boundary for River Rch & Prof#=Deadman 39,Reach-1,4
Up Type=0
Dn Type=3
Dn Slope=0.005
Boundary for River Rch & Prof#=Deadman 39,Reach-1,5
Up Type=0
Dn Type=3
Dn Slope=0.005
Boundary for River Rch & Prof#=Deadman 39,Reach-1,6
Up Type=0
Dn Type=3
Dn Slope=0.005
Boundary for River Rch & Prof#=Deadman 39,Reach-1,7
Up Type=0
Dn Type=3
Dn Slope=0.005

--- Deadman 39.g01 (geometry) ---

Geom Title=Existing Conditions

River Reach=Deadman 39,Reach-1
Reach XY= 30
      1640855.00      6914238.00      1640949.13      6914240.10
      1641015.50      6914286.79      1641153.53      6914291.55
      1641245.64      6914377.07      1641303.38      6914399.83
      1641307.24      6914632.07      1641398.92      6914785.80
      1641411.12      6914840.18      1641451.26      6914889.56
      1641455.50      6914927.83      1641451.26      6915036.44
      1641411.14      6915085.83      1641396.84      6915144.05
      1641307.06      6915243.86      1641305.39      6915522.84
      1641396.84      6915631.95      1641411.14      6915690.17
      1641451.25      6915739.55      1641455.53      6915898.25
      1641447.33      6915944.52      1641399.35      6915986.03
      1641148.79      6915995.80      1641065.77      6916078.30
      1641046.85      6916144.06      1640985.23      6916208.41
      1640874.62      6916267.53      1640812.48      6916387.99
      1640852.66      6916443.77      1640855.00      6916538.00

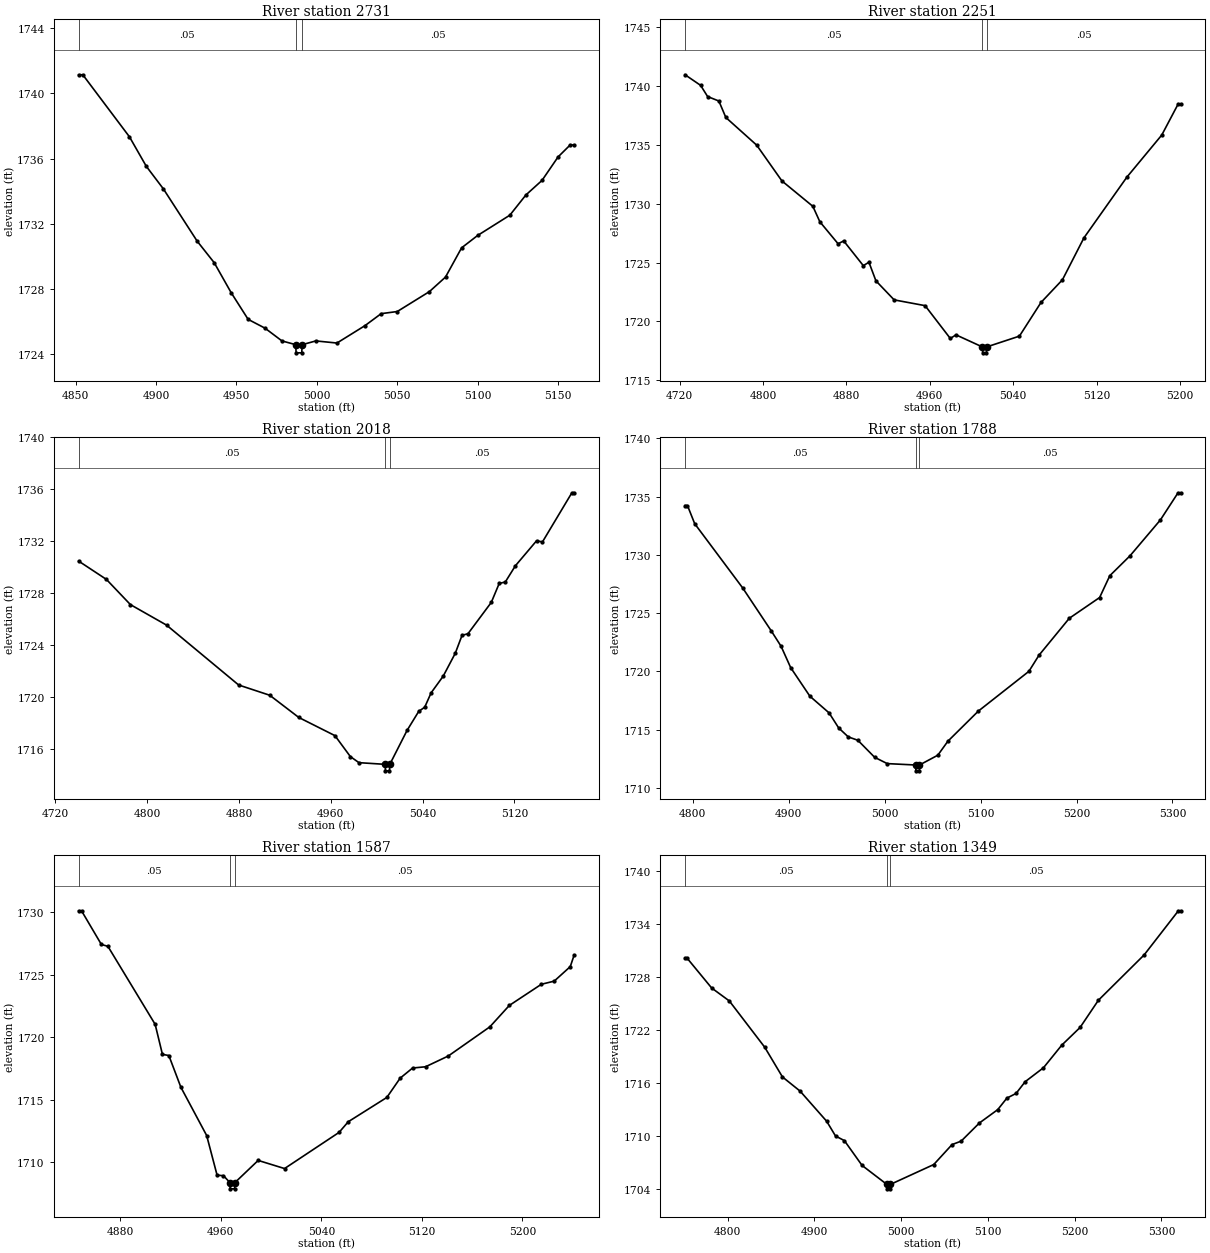
Type RM Length L Ch R = 1,2731,480,480,480
BEGIN DESCRIPTION:
Deadman 39 6.0
END DESCRIPTION:
XS GIS Cut Line= 3
      1641155.05      6914437.98      1641305.00      6914388.00
      1641455.03      6914388.00
#Sta/Elev= 30
  4851.9 1741.13  4854.5 1741.13  4883.5 1737.33  4894.0 1735.52  4904.6 1734.14
  4925.6 1730.94  4936.2 1729.62  4946.7 1727.79  4957.3 1726.15  4967.8 1725.61
  4978.3 1724.83  4986.9 1724.60  4987.1 1724.10  4990.6 1724.10  4990.9 1724.60
  4999.4 1724.83  5012.5 1724.70  5030.0 1725.77  5040.0 1726.50  5050.0 1726.63
  5070.0 1727.85  5080.0 1728.74  5090.0 1730.53  5100.0 1731.29  5120.0 1732.53
  5130.0 1733.77  5140.0 1734.66  5150.0 1736.10  5157.5 1736.83  5160.0 1736.83
#Mann=3,-1,0
  4851.9    0.05       0  4986.9    0.05       0  4990.9    0.05       0
Bank Sta=4986.9,4990.9
Exp/Cntr=0.3,0.1

Type RM Length L Ch R = 1,2251,233,233,233
BEGIN DESCRIPTION:
Deadman 39 5.0
END DESCRIPTION:
XS GIS Cut Line= 3
      1641154.96      6914737.98      1641405.00      6914838.00
      1641605.04      6914787.99
#Sta/Elev= 30
  4725.2 1740.96  4740.1 1740.06  4746.8 1739.11  4757.6 1738.73  4764.3 1737.33
  4793.9 1734.98  4818.1 1731.94  4847.8 1729.78  4854.5 1728.47  4872.0 1726.60
  4877.4 1726.84  4896.2 1724.74  4901.6 1725.03  4908.3 1723.45  4925.8 1721.83
  4955.5 1721.34  4979.7 1718.55  4985.1 1718.86  5010.5 1717.83  5010.8 1717.33
  5014.3 1717.33  5014.5 1717.83  5046.0 1718.75  5066.7 1721.61  5087.3 1723.54
  5107.9 1727.10  5149.1 1732.26  5182.6 1735.84  5198.1 1738.44  5200.7 1738.44
#Mann=3,-1,0
  4725.2    0.05       0  5010.5    0.05       0  5014.5    0.05       0
Bank Sta=5010.5,5014.5
Exp/Cntr=0.3,0.1

Type RM Length L Ch R = 1,2018,230,230,230
BEGIN DESCRIPTION:
Mapping XS d32fbb8c
END DESCRIPTION:
XS GIS Cut Line= 2
      1641191.95      6914972.95      1641603.91      6915102.00
#Sta/Elev= 30
  4740.3 1730.46  4764.5 1729.05  4785.4 1727.11  4816.9 1725.53  4879.7 1720.92
  4906.8 1720.13  4932.1 1718.42  4963.6 1717.02  4977.0 1715.41  4984.5 1714.94
  5007.4 1714.81  5007.6 1714.31  5011.1 1714.31  5011.4 1714.81  5026.4 1717.42
  5036.6 1718.89  5041.8 1719.21  5047.4 1720.32  5057.9 1721.60  5068.4 1723.36
  5074.3 1724.74  5079.5 1724.87  5099.8 1727.28  5106.7 1728.74  5112.0 1728.85
  5120.8 1730.10  5139.2 1732.02  5144.4 1731.94  5170.0 1735.72  5172.0 1735.72
#Mann=3,-1,0
  4740.3    0.05       0  5007.4    0.05       0  5011.4    0.05       0
Bank Sta=5007.4,5011.4
Exp/Cntr=0.3,0.1

Type RM Length L Ch R = 1,1788,201,201,201
BEGIN DESCRIPTION:
Deadman 39 4.0
END DESCRIPTION:
XS GIS Cut Line= 3
      1641104.95      6915238.00      1641305.00      6915238.00
      1641605.02      6915137.99
#Sta/Elev= 30
  4792.2 1734.22  4794.7 1734.22  4802.2 1732.67  4852.2 1727.16  4882.2 1723.45
  4892.2 1722.16  4902.2 1720.33  4922.2 1717.88  4942.2 1716.45  4952.2 1715.16
  4962.2 1714.39  4972.2 1714.10  4989.7 1712.64  5002.8 1712.10  5032.4 1711.98
  5032.7 1711.48  5036.2 1711.48  5036.4 1711.98  5055.5 1712.82  5066.0 1714.02
  5097.7 1716.60  5150.4 1720.01  5160.9 1721.39  5192.5 1724.56  5224.1 1726.34
  5234.7 1728.21  5255.8 1729.92  5287.4 1732.99  5305.8 1735.32  5308.5 1735.32
#Mann=3,-1,0
  4792.2    0.05       0  5032.4    0.05       0  5036.4    0.05       0
Bank Sta=5032.4,5036.4
Exp/Cntr=0.3,0.1

Type RM Length L Ch R = 1,1587,238,238,238
BEGIN DESCRIPTION:
Mapping XS 6ee10caf
END DESCRIPTION:
XS GIS Cut Line= 2
      1641155.55      6915467.68      1641540.48      6915381.77
#Sta/Elev= 30
  4846.8 1730.10  4849.1 1730.10  4864.9 1727.41  4870.1 1727.26  4907.7 1721.03
  4913.5 1718.63  4918.6 1718.54  4928.2 1716.00  4948.7 1712.15  4957.0 1708.98
  4962.1 1708.94  4967.2 1708.39  4967.4 1707.89  4970.9 1707.89  4971.2 1708.39
  4989.7 1710.16  5010.7 1709.51  5054.1 1712.40  5061.4 1713.25  5092.1 1715.19
  5102.7 1716.73  5112.6 1717.54  5122.9 1717.64  5141.0 1718.50  5174.1 1720.83
  5189.6 1722.54  5215.1 1724.23  5225.3 1724.48  5238.1 1725.64  5241.2 1726.57
#Mann=3,-1,0
  4846.8    0.05       0  4967.2    0.05       0  4971.2    0.05       0
Bank Sta=4967.2,4971.2
Exp/Cntr=0.3,0.1

Type RM Length L Ch R = 1,1349,301,301,301
BEGIN DESCRIPTION:
Deadman 39 3.0
END DESCRIPTION:
XS GIS Cut Line= 3
      1641154.96      6915587.99      1641405.00      6915638.00
      1641704.98      6915538.01
#Sta/Elev= 30
  4751.0 1730.07  4753.6 1730.07  4781.6 1726.73  4802.0 1725.26  4842.8 1720.02
  4863.2 1716.66  4883.6 1715.05  4914.2 1711.64  4924.4 1709.97  4934.6 1709.45
  4955.0 1706.64  4983.6 1704.49  4983.8 1703.99  4987.3 1703.99  4987.6 1704.49
  5037.6 1706.74  5058.7 1709.00  5069.2 1709.39  5090.3 1711.45  5111.4 1712.96
  5121.9 1714.26  5132.5 1714.79  5143.0 1716.12  5164.1 1717.70  5185.2 1720.26
  5206.3 1722.26  5227.4 1725.34  5280.1 1730.47  5319.6 1735.47  5322.2 1735.47
#Mann=3,-1,0
  4751.0    0.05       0  4983.6    0.05       0  4987.6    0.05       0
Bank Sta=4983.6,4987.6
Exp/Cntr=0.3,0.1

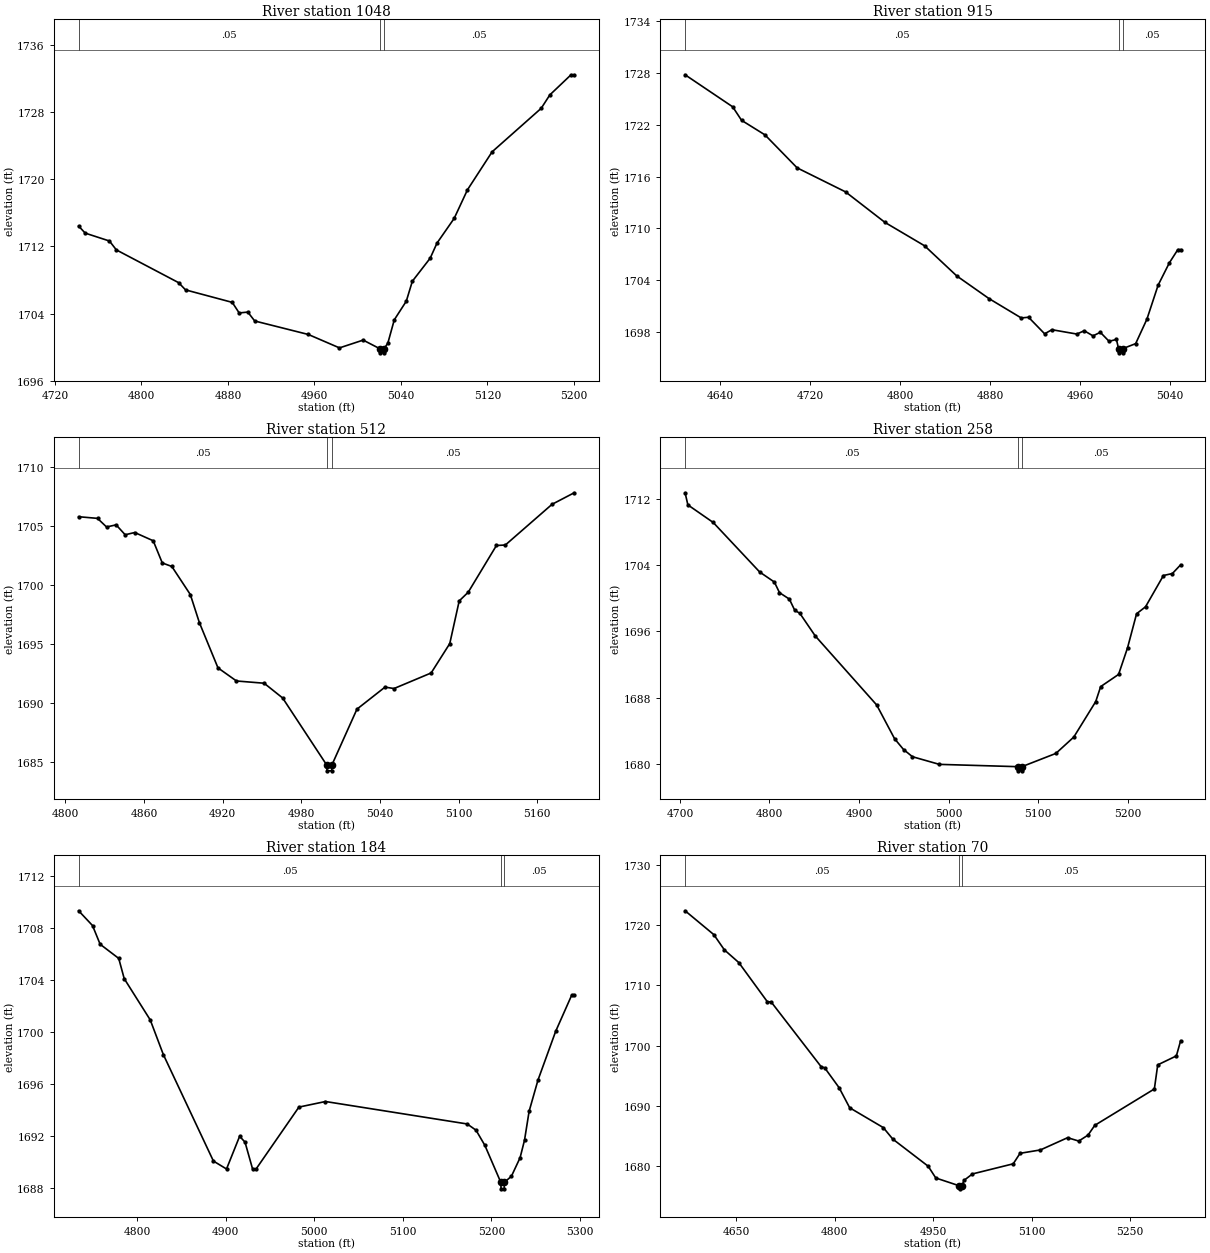
Type RM Length L Ch R = 1,1048,133,133,133
BEGIN DESCRIPTION:
Mapping XS e6d35e70
END DESCRIPTION:
XS GIS Cut Line= 3
      1641251.49      6915762.20      1641443.44      6915916.09
      1641635.34      6916007.08
#Sta/Elev= 30
  4741.9 1714.43  4748.0 1713.59  4770.4 1712.65  4776.8 1711.59  4834.4 1707.68
  4840.8 1706.82  4884.0 1705.33  4890.4 1704.07  4898.4 1704.17  4904.8 1703.11
  4954.4 1701.50  4983.2 1699.90  5005.1 1700.83  5020.4 1699.81  5020.6 1699.31
  5024.1 1699.31  5024.4 1699.81  5027.9 1700.45  5033.9 1703.25  5045.0 1705.47
  5050.6 1707.85  5067.1 1710.60  5073.4 1712.40  5089.3 1715.35  5101.6 1718.76
  5124.4 1723.29  5169.8 1728.48  5177.8 1730.08  5197.4 1732.48  5200.3 1732.48
#Mann=3,-1,0
  4741.9    0.05       0  5020.4    0.05       0  5024.4    0.05       0
Bank Sta=5020.4,5024.4
Exp/Cntr=0.3,0.1

Type RM Length L Ch R = 1,915,403,403,403
BEGIN DESCRIPTION:
Deadman 39 2.0
END DESCRIPTION:
XS GIS Cut Line= 3
      1641104.98      6915687.97      1641355.00      6915988.00
      1641355.00      6916037.95
#Sta/Elev= 30
  4609.0 1727.75  4651.3 1724.05  4659.2 1722.49  4680.0 1720.81  4708.6 1717.00
  4751.6 1714.23  4786.7 1710.70  4821.9 1708.00  4850.5 1704.52  4879.1 1701.91
  4907.8 1699.67  4914.3 1699.75  4928.6 1697.84  4935.1 1698.31  4957.2 1697.81
  4963.8 1698.19  4971.6 1697.60  4978.1 1698.01  4985.9 1696.97  4992.4 1697.19
  4994.3 1696.14  4994.5 1695.64  4998.0 1695.64  4998.3 1696.14  5009.5 1696.70
  5019.5 1699.52  5029.5 1703.46  5039.5 1706.04  5047.0 1707.56  5049.5 1707.56
#Mann=3,-1,0
  4609.0    0.05       0  4994.3    0.05       0  4998.3    0.05       0
Bank Sta=4994.3,4998.3
Exp/Cntr=0.3,0.1

Type RM Length L Ch R = 1,512,254,254,254
BEGIN DESCRIPTION:
Mapping XS 44fafbd9
END DESCRIPTION:
XS GIS Cut Line= 2
      1640902.39      6916020.35      1641177.02      6916280.09
#Sta/Elev= 30
  4810.1 1705.82  4824.5 1705.68  4831.4 1704.95  4838.7 1705.13  4845.6 1704.29
  4852.9 1704.48  4867.0 1703.78  4873.9 1701.90  4881.2 1701.60  4895.3 1699.22
  4902.2 1696.84  4916.4 1693.00  4930.5 1691.89  4951.6 1691.70  4965.7 1690.45
  4999.3 1684.77  4999.6 1684.27  5003.1 1684.27  5003.3 1684.77  5022.4 1689.50
  5043.8 1691.37  5050.7 1691.25  5079.0 1692.57  5093.2 1695.06  5100.4 1698.68
  5107.3 1699.42  5128.8 1703.38  5135.6 1703.42  5171.2 1706.87  5188.1 1707.85
#Mann=3,-1,0
  4810.1    0.05       0  4999.3    0.05       0  5003.3    0.05       0
Bank Sta=4999.3,5003.3
Exp/Cntr=0.3,0.1

Type RM Length L Ch R = 1,258,74,74,74
BEGIN DESCRIPTION:
Mapping XS 67269a23
END DESCRIPTION:
XS GIS Cut Line= 3
      1640579.69      6916220.53      1640755.11      6916303.27
      1641114.21      6916316.51
#Sta/Elev= 30
  4705.8 1712.71  4708.9 1711.25  4737.2 1709.13  4789.1 1703.16  4805.5 1701.95
  4811.2 1700.67  4822.2 1699.90  4828.3 1698.53  4833.8 1698.20  4851.1 1695.46
  4919.7 1687.14  4939.7 1683.07  4949.7 1681.77  4959.7 1680.90  4989.7 1679.98
  5077.8 1679.70  5078.0 1679.20  5081.5 1679.20  5081.8 1679.70  5119.8 1681.30
  5139.8 1683.27  5164.3 1687.55  5169.8 1689.35  5189.8 1690.82  5199.8 1694.02
  5209.9 1698.13  5219.9 1698.97  5239.9 1702.74  5249.9 1702.98  5259.1 1704.03
#Mann=3,-1,0
  4705.8    0.05       0  5077.8    0.05       0  5081.8    0.05       0
Bank Sta=5077.8,5081.8
Exp/Cntr=0.3,0.1

Type RM Length L Ch R = 1,184,114,114,114
BEGIN DESCRIPTION:
Mapping XS 232bd136
END DESCRIPTION:
XS GIS Cut Line= 3
      1640592.95      6916256.94      1640756.76      6916372.77
      1641115.85      6916361.19
#Sta/Elev= 30
  4733.7 1709.33  4749.4 1708.19  4758.0 1706.75  4779.0 1705.66  4785.2 1704.10
  4814.6 1700.92  4829.4 1698.25  4886.0 1690.04  4900.8 1689.43  4915.6 1691.95
  4921.7 1691.50  4930.2 1689.44  4934.3 1689.44  4982.6 1694.20  5012.6 1694.63
  5172.7 1692.90  5182.7 1692.42  5192.7 1691.25  5210.7 1688.40  5211.0 1687.90
  5214.5 1687.90  5214.7 1688.40  5222.7 1688.87  5232.5 1690.30  5237.5 1691.65
  5242.7 1693.88  5252.7 1696.28  5272.7 1700.04  5290.7 1702.81  5293.6 1702.81
#Mann=3,-1,0
  4733.7    0.05       0  5210.7    0.05       0  5214.7    0.05       0
Bank Sta=5210.7,5214.7
Exp/Cntr=0.3,0.1

Type RM Length L Ch R = 1,70,0,0,0
BEGIN DESCRIPTION:
Deadman 39 1.0
END DESCRIPTION:
XS GIS Cut Line= 3
      1640480.00      6916263.00      1640855.53      6916467.70
      1641171.26      6916383.36
#Sta/Elev= 30
  4572.3 1722.37  4616.0 1718.42  4632.1 1715.89  4654.0 1713.79  4697.6 1707.28
  4703.3 1707.26  4779.3 1696.54  4785.0 1696.31  4806.8 1693.04  4822.9 1689.71
  4874.1 1686.42  4888.5 1684.52  4942.4 1680.02  4954.0 1678.07  4989.9 1676.77
  4990.2 1676.27  4993.9 1676.77  4996.8 1677.66  5009.8 1678.74  5071.9 1680.42
  5082.3 1682.16  5113.3 1682.72  5154.7 1684.75  5171.7 1684.19  5185.8 1685.18
  5196.1 1686.80  5286.8 1692.83  5291.9 1696.82  5320.3 1698.31  5326.8 1700.82
#Mann=3,-1,0
  4572.3    0.05       0  4989.9    0.05       0  4993.9    0.05       0
Bank Sta=4989.9,4993.9
Exp/Cntr=0.3,0.1

Chan Stop Cuts=-1