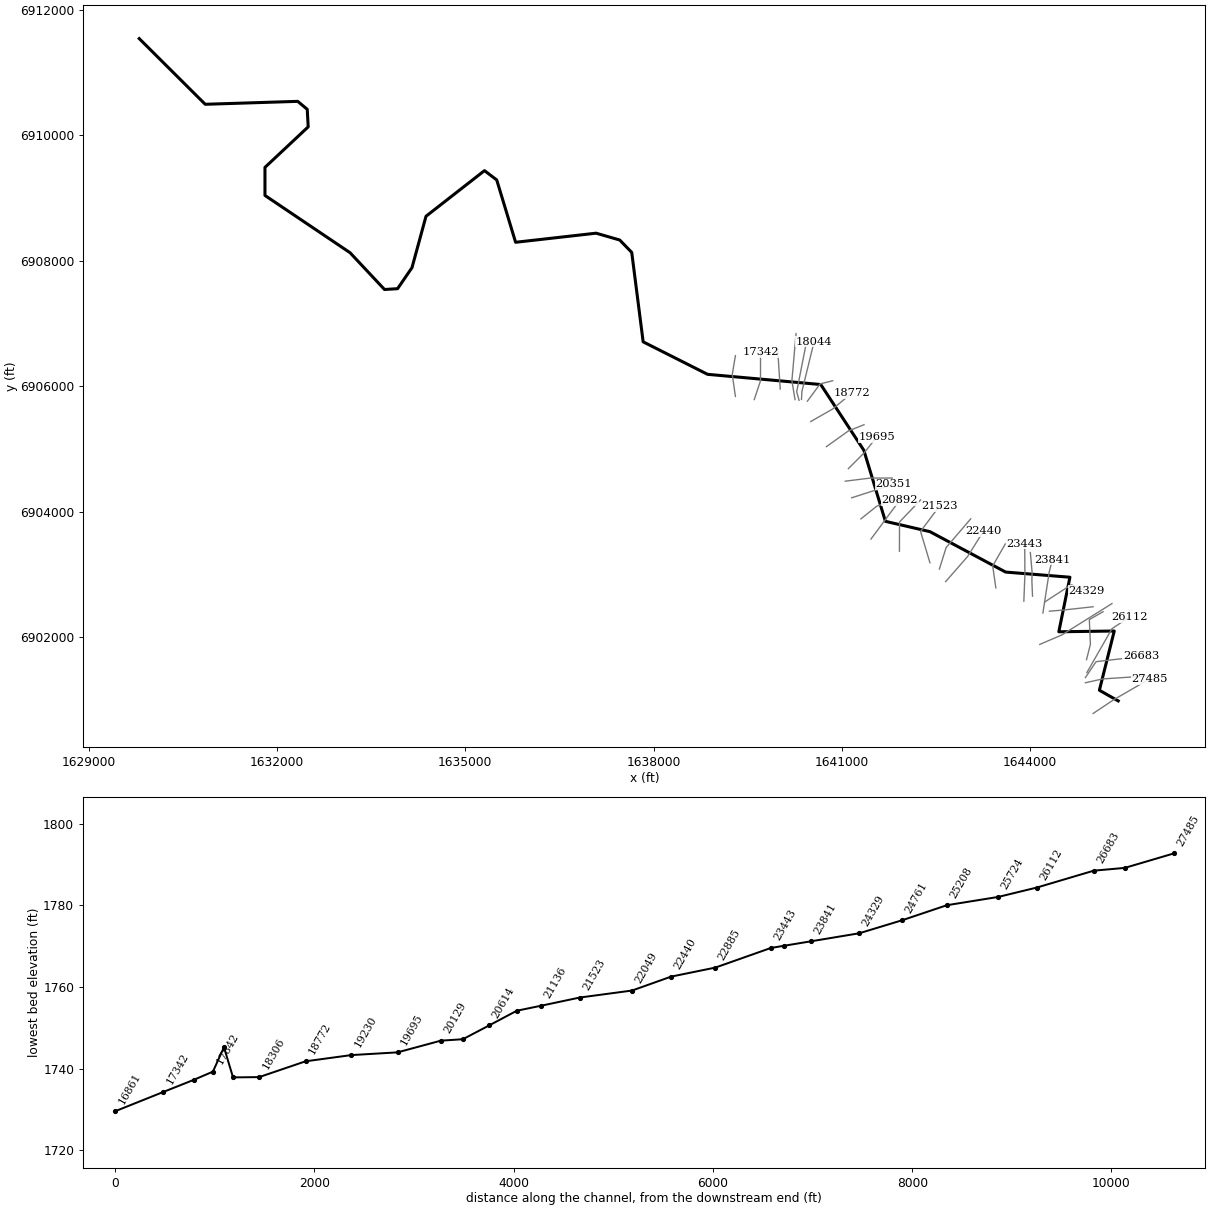
--- Deadman 40.prj (project) ---

Proj Title=Deadman 40 Base Level Engineering
Current Plan=p01
Default Exp/Contr=0.3,0.1
English Units
Geom File=g01
Flow File=f01
Plan File=p01
BEGIN DESCRIPTION:
Deadman 40
END DESCRIPTION:

--- Deadman 40.p01 (plan) ---

Plan Title=Multiple Run
Short Identifier=Multiple
Geom File=g01
Flow File=f01
Subcritical Flow
K Sum by GR= 0
Std Step Tol= 0.01
Critical Tol= 0.01
Num of Std Step Trials= 20
Max Error Tol= 0.3
Flow Tol Ratio= 0.001
Split Flow NTrial= 30
Split Flow Tol= 0.02
Split Flow Ratio= 0.02
Log Output Level= 0
Friction Slope Method= 1
Unsteady Friction Slope Method= 2
Unsteady Bridges Friction Slope Method= 1
Parabolic Critical Depth
Global Vel Dist=  1 , 1 , 1
Global Log Level= 0
CheckData=True
Encroach Param= -1, 0, 0, 0
BEGIN DESCRIPTION:
Multiple Run
END DESCRIPTION:

--- Deadman 40.f01 (steady flow) ---

Flow Title=Multiple
Number of Profiles=7
Profile Names=10-year,25-year,50-year,1pct_min,100-year,1pct_plu,500-year
River Rch & RM= Deadman 40,Reach-1,27485
     315     439     542     333     664    1326    1011
River Rch & RM= Deadman 40,Reach-1,19695
     437     621     776     482     961    1918    1496
River Rch & RM= Deadman 40,Reach-1,18044
     520     742     931     580    1157    2309    1813
River Rch & RM= Deadman 40,Reach-1,8257
     717    1039    1316     827    1650    3293    2631
Boundary for River Rch & Prof#=Deadman 40,Reach-1,1
Up Type=0
Dn Type=3
Dn Slope=0.005
Boundary for River Rch & Prof#=Deadman 40,Reach-1,2
Up Type=0
Dn Type=3
Dn Slope=0.005
Boundary for River Rch & Prof#=Deadman 40,Reach-1,3
Up Type=0
Dn Type=3
Dn Slope=0.005
Boundary for River Rch & Prof#=Deadman 40,Reach-1,4
Up Type=0
Dn Type=3
Dn Slope=0.005
Boundary for River Rch & Prof#=Deadman 40,Reach-1,5
Up Type=0
Dn Type=3
Dn Slope=0.005
Boundary for River Rch & Prof#=Deadman 40,Reach-1,6
Up Type=0
Dn Type=3
Dn Slope=0.005
Boundary for River Rch & Prof#=Deadman 40,Reach-1,7
Up Type=0
Dn Type=3
Dn Slope=0.005

--- Deadman 40.g01 (geometry) ---

Geom Title=Existing Conditions

River Reach=Deadman 40,Reach-1
Reach XY= 30
      1645405.00      6900988.00      1645104.94      6901157.99
      1645341.64      6902101.35      1644458.53      6902089.45
      1644635.42      6902958.21      1643610.94      6903040.26
      1642403.54      6903684.46      1641695.20      6903848.48
      1641351.81      6904979.65      1640665.12      6906027.65
      1638860.94      6906190.26      1637834.91      6906707.79
      1637652.94      6908132.15      1637461.06      6908329.86
      1637084.85      6908438.37      1635802.53      6908293.46
      1635501.46      6909286.54      1635306.65      6909434.90
      1634374.78      6908708.09      1634151.45      6907889.47
      1633921.80      6907554.42      1633713.44      6907541.40
      1633164.70      6908127.23      1631808.54      6909039.46
      1631808.55      6909486.53      1632497.19      6910131.81
      1632482.14      6910411.53      1632330.11      6910538.32
      1630856.46      6910491.54      1629805.00      6911538.00

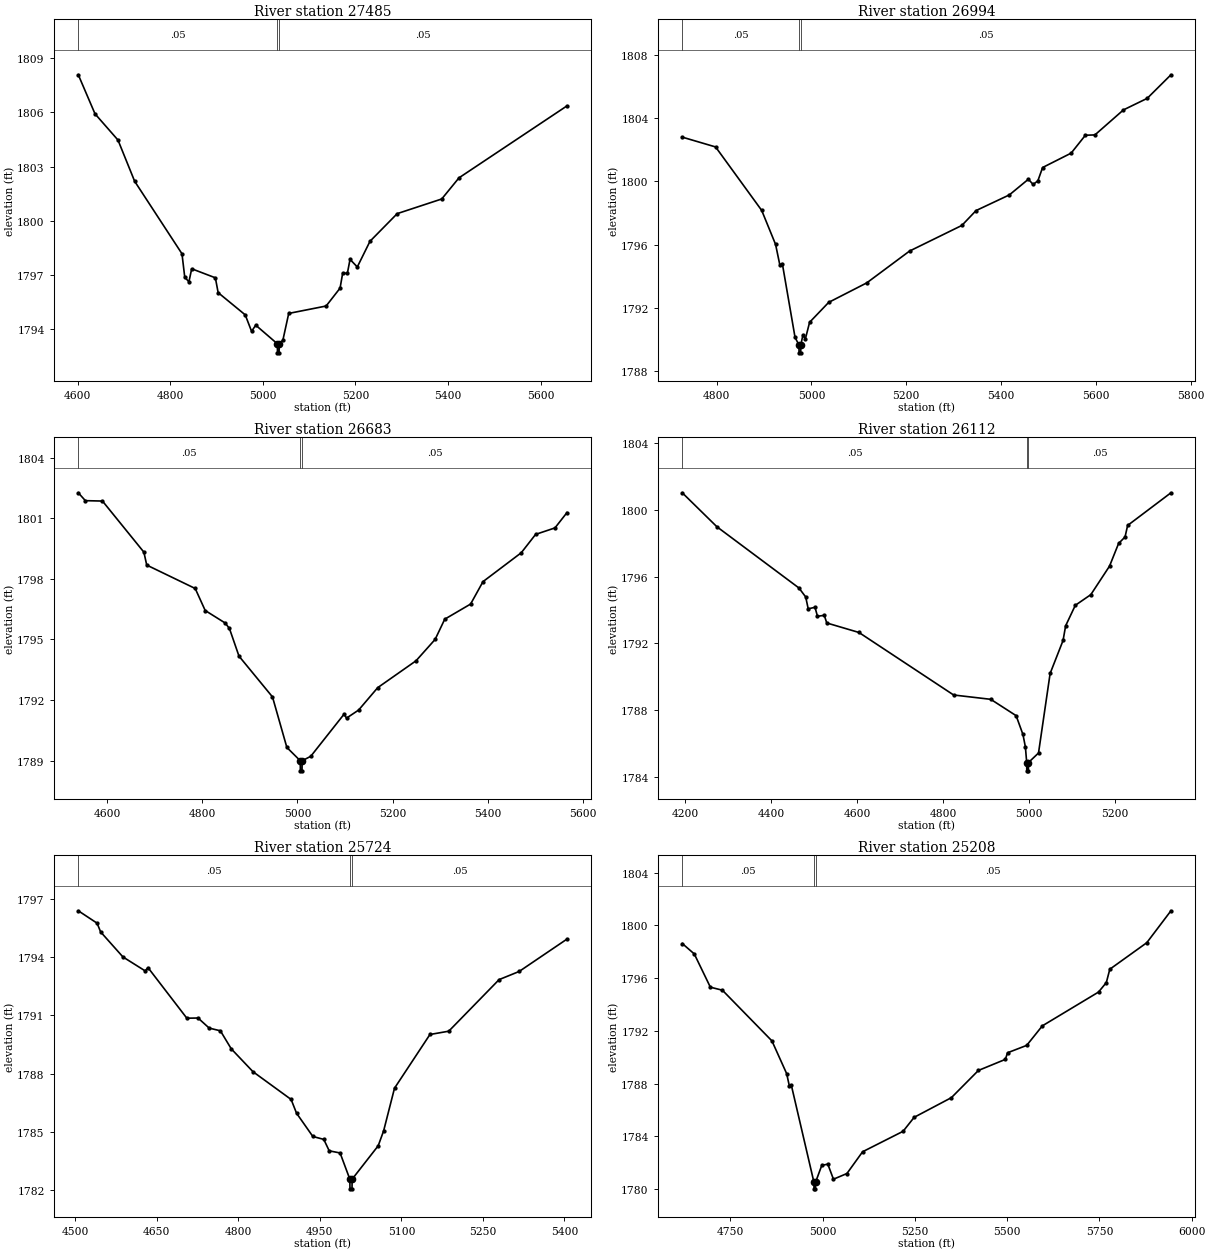
Type RM Length L Ch R = 1,27485,491,491,491
BEGIN DESCRIPTION:
Deadman 40 57.0
END DESCRIPTION:
XS GIS Cut Line= 3
      1645004.98      6900787.99      1645336.49      6901008.77
      1645905.04      6901338.02
#Sta/Elev= 30
  4601.7 1808.08  4637.8 1805.92  4687.4 1804.47  4723.4 1802.19  4825.6 1798.18
  4831.6 1796.88  4840.6 1796.63  4846.6 1797.35  4897.7 1796.85  4903.7 1796.03
  4962.2 1794.80  4975.9 1793.89  4984.9 1794.23  5031.6 1793.20  5031.8 1792.70
  5035.3 1792.70  5035.6 1793.20  5043.5 1793.40  5056.1 1794.88  5136.9 1795.29
  5167.0 1796.28  5172.7 1797.12  5182.7 1797.09  5188.5 1797.87  5204.2 1797.45
  5231.6 1798.87  5290.4 1800.40  5386.5 1801.21  5423.8 1802.38  5657.0 1806.36
#Mann=3,-1,0
  4601.7    0.05       0  5031.6    0.03       0  5035.6    0.05       0
Bank Sta=5031.6,5035.6
Exp/Cntr=0.3,0.1

Type RM Length L Ch R = 1,26994,311,311,311
BEGIN DESCRIPTION:
Deadman 40 56.0
END DESCRIPTION:
XS GIS Cut Line= 3
      1644882.89      6901277.39      1645155.00      6901338.00
      1645904.96      6901388.00
#Sta/Elev= 30
  4727.7 1802.80  4798.0 1802.18  4895.2 1798.17  4924.5 1796.02  4933.6 1794.70
  4938.7 1794.81  4965.5 1790.15  4973.7 1789.67  4974.0 1789.17  4977.5 1789.17
  4977.7 1789.67  4982.2 1790.31  4987.3 1790.05  4996.2 1791.10  5036.5 1792.36
  5116.7 1793.59  5206.9 1795.60  5317.2 1797.22  5347.2 1798.16  5417.4 1799.15
  5457.5 1800.14  5467.5 1799.81  5477.5 1800.04  5487.5 1800.88  5547.7 1801.79
  5577.7 1802.92  5597.8 1802.94  5657.9 1804.52  5708.0 1805.25  5758.1 1806.74
#Mann=3,-1,0
  4727.7    0.05       0  4973.7    0.03       0  4977.7    0.05       0
Bank Sta=4973.7,4977.7
Exp/Cntr=0.3,0.1

Type RM Length L Ch R = 1,26683,571,571,571
BEGIN DESCRIPTION:
Mapping XS 4ab54424
END DESCRIPTION:
XS GIS Cut Line= 3
      1644882.25      6901359.75      1645052.37      6901613.20
      1645770.51      6901696.46
#Sta/Elev= 30
  4538.8 1802.26  4553.7 1801.87  4589.7 1801.85  4676.8 1799.32  4682.8 1798.68
  4784.8 1797.52  4805.8 1796.43  4847.9 1795.81  4856.8 1795.54  4876.9 1794.17
  4947.4 1792.15  4977.6 1789.65  5005.8 1788.99  5006.0 1788.49  5009.5 1788.49
  5009.8 1788.99  5027.9 1789.21  5098.1 1791.30  5103.1 1791.10  5128.6 1791.50
  5168.8 1792.61  5249.4 1793.94  5289.6 1795.00  5309.8 1796.00  5364.2 1796.75
  5390.3 1797.86  5470.8 1799.29  5501.0 1800.20  5541.7 1800.52  5567.0 1801.28
#Mann=3,-1,0
  4538.8    0.05       0  5005.8    0.05       0  5009.8    0.05       0
Bank Sta=5005.8,5009.8
Exp/Cntr=0.3,0.1

Type RM Length L Ch R = 1,26112,388,388,388
BEGIN DESCRIPTION:
Deadman 40 55.0
END DESCRIPTION:
XS GIS Cut Line= 3
      1644904.98      6901437.97      1645305.00      6902138.00
      1645580.07      6902321.47
#Sta/Elev= 30
  4193.6 1801.04  4274.3 1799.00  4465.0 1795.33  4480.8 1794.79  4486.6 1794.08
  4502.4 1794.17  4508.2 1793.63  4524.0 1793.69  4529.8 1793.23  4604.7 1792.66
  4824.9 1788.91  4911.3 1788.65  4970.3 1787.67  4986.2 1786.54  4991.9 1785.79
  4994.9 1784.86  4995.1 1784.36  4998.8 1784.36  4999.1 1784.86  5022.4 1785.43
  5049.4 1790.20  5079.5 1792.18  5085.5 1793.06  5108.0 1794.29  5144.1 1794.93
  5187.6 1796.64  5208.7 1798.00  5223.7 1798.39  5229.7 1799.08  5330.5 1801.04
#Mann=3,-1,0
  4193.6    0.05       0  4994.9    0.05       0  4999.1    0.05       0
Bank Sta=4994.9,4999.1
Exp/Cntr=0.3,0.1

Type RM Length L Ch R = 1,25724,516,516,516
BEGIN DESCRIPTION:
Mapping XS d311ec33
END DESCRIPTION:
XS GIS Cut Line= 4
      1644899.59      6901644.44      1644962.09      6901890.97
      1644944.73      6902283.33      1645163.46      6902408.32
#Sta/Elev= 30
  4505.6 1796.40  4540.2 1795.76  4546.7 1795.31  4587.7 1794.02  4628.6 1793.30
  4633.8 1793.47  4705.3 1790.86  4725.9 1790.87  4746.4 1790.35  4767.0 1790.21
  4787.0 1789.28  4827.0 1788.10  4897.1 1786.67  4907.1 1785.96  4937.1 1784.76
  4957.2 1784.61  4967.2 1784.02  4987.2 1783.91  5005.1 1782.56  5005.4 1782.06
  5009.1 1782.06  5009.4 1782.56  5057.3 1784.28  5067.3 1785.05  5087.3 1787.25
  5152.5 1790.02  5187.1 1790.19  5279.7 1792.85  5316.6 1793.27  5404.6 1794.94
#Mann=3,-1,0
  4505.6    0.05       0  5005.1    0.05       0  5009.4    0.05       0
Bank Sta=5005.1,5009.4
Exp/Cntr=0.3,0.1

Type RM Length L Ch R = 1,25208,447,447,447
BEGIN DESCRIPTION:
Deadman 40 54.0
END DESCRIPTION:
XS GIS Cut Line= 3
      1644154.99      6901888.00      1644505.00      6902038.00
      1645305.00      6902538.00
#Sta/Elev= 30
  4619.7 1798.62  4652.3 1797.83  4695.9 1795.31  4728.5 1795.08  4862.7 1791.24
  4902.6 1788.76  4909.8 1787.84  4915.3 1787.88  4976.5 1780.53  4976.8 1780.03
  4980.6 1780.03  4980.9 1780.53  4997.8 1781.81  5014.1 1781.90  5029.4 1780.76
  5065.9 1781.19  5108.4 1782.84  5218.1 1784.39  5248.1 1785.45  5349.0 1786.94
  5422.1 1789.00  5495.2 1789.84  5501.1 1790.34  5553.0 1790.90  5595.4 1792.38
  5747.6 1794.94  5768.8 1795.66  5778.2 1796.67  5878.4 1798.68  5943.9 1801.10
#Mann=3,-1,0
  4619.7    0.05       0  4976.5    0.05       0  4980.9    0.05       0
Bank Sta=4976.5,4980.9
Exp/Cntr=0.3,0.1

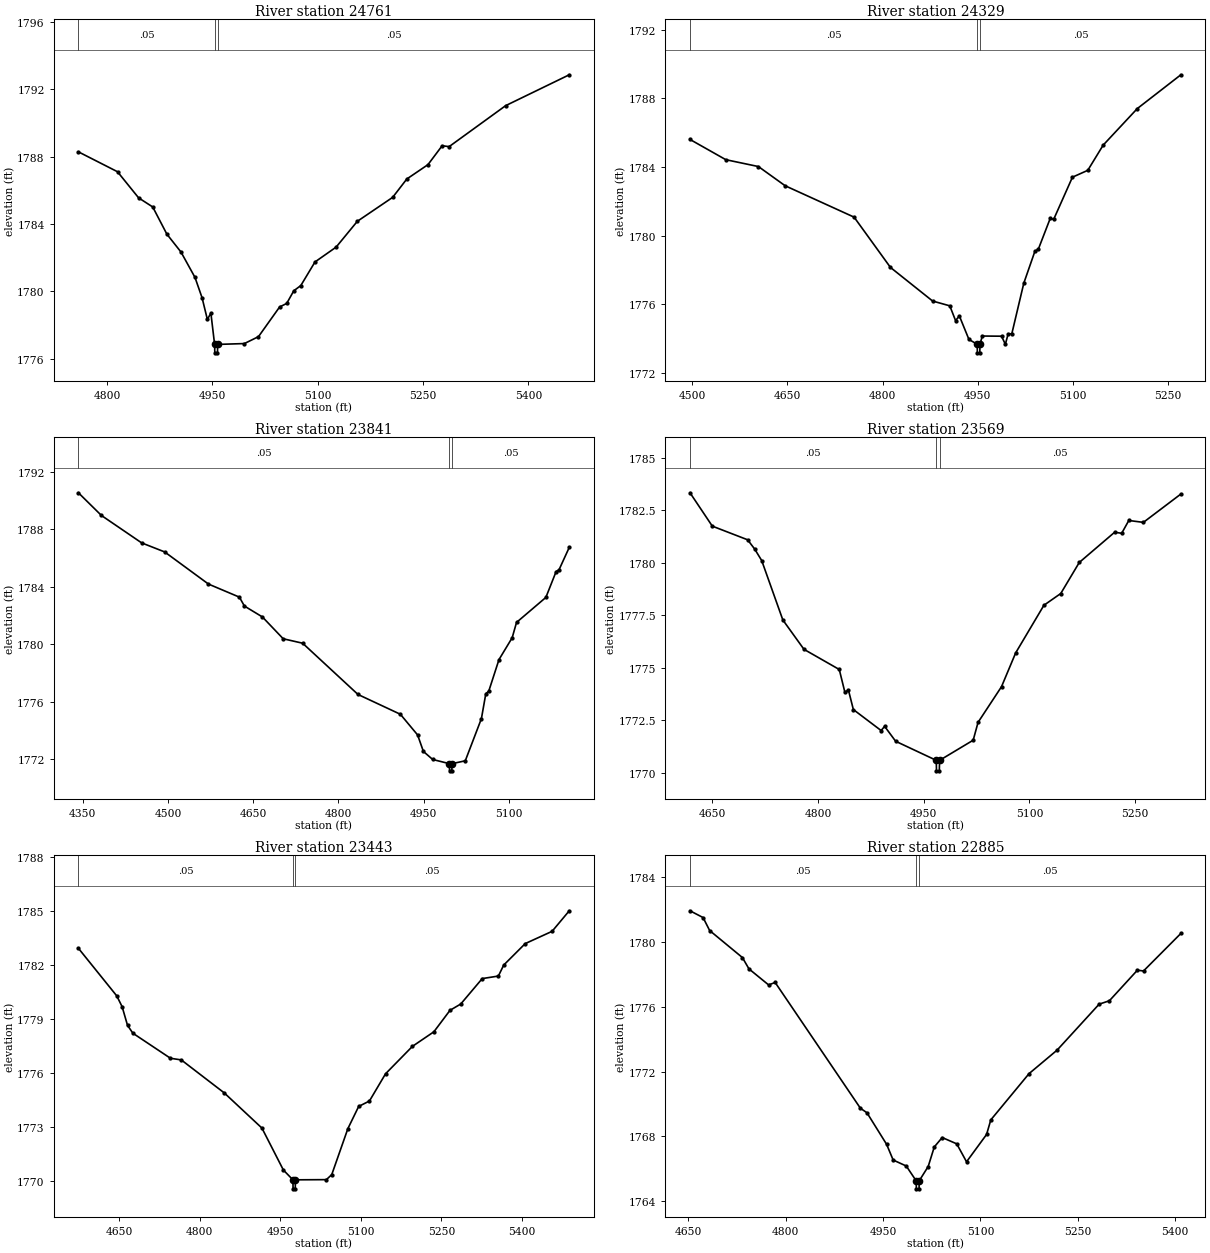
Type RM Length L Ch R = 1,24761,432,432,432
BEGIN DESCRIPTION:
Deadman 40 53.0
END DESCRIPTION:
XS GIS Cut Line= 3
      1644309.45      6902417.55      1644555.00      6902438.00
      1645005.03      6902488.00
#Sta/Elev= 30
  4759.1 1788.28  4814.8 1787.10  4844.9 1785.55  4865.0 1785.01  4885.1 1783.40
  4905.2 1782.34  4925.2 1780.83  4935.3 1779.62  4942.8 1778.34  4947.8 1778.72
  4953.1 1776.86  4953.4 1776.36  4957.2 1776.36  4957.5 1776.86  4995.5 1776.91
  5015.6 1777.32  5045.7 1779.08  5055.8 1779.29  5065.9 1780.04  5075.9 1780.35
  5096.1 1781.75  5126.2 1782.63  5156.4 1784.16  5206.7 1785.58  5226.9 1786.67
  5257.0 1787.52  5277.2 1788.64  5287.2 1788.59  5367.7 1791.02  5458.3 1792.85
#Mann=3,-1,0
  4759.1    0.05       0  4953.1    0.05       0  4957.5    0.05       0
Bank Sta=4953.1,4957.5
Exp/Cntr=0.3,0.1

Type RM Length L Ch R = 1,24329,488,488,488
BEGIN DESCRIPTION:
Deadman 40 52.0
END DESCRIPTION:
XS GIS Cut Line= 3
      1644231.89      6902562.63      1644655.00      6902838.00
      1644905.02      6902737.99
#Sta/Elev= 30
  4496.3 1785.60  4552.8 1784.42  4604.2 1784.02  4646.4 1782.90  4755.1 1781.07
  4812.4 1778.14  4878.9 1776.18  4906.0 1775.90  4915.1 1775.04  4921.1 1775.31
  4936.2 1773.94  4949.2 1773.66  4949.5 1773.16  4953.3 1773.16  4953.6 1773.66
  4957.3 1774.14  4987.6 1774.13  4993.6 1773.66  4998.1 1774.27  5003.8 1774.27
  5022.7 1777.22  5040.2 1779.08  5045.6 1779.20  5064.4 1781.00  5069.8 1780.94
  5099.4 1783.40  5123.6 1783.80  5147.9 1785.27  5201.7 1787.40  5270.4 1789.37
#Mann=3,-1,0
  4496.3    0.05       0  4949.2    0.05       0  4953.6    0.05       0
Bank Sta=4949.2,4953.6
Exp/Cntr=0.3,0.1

Type RM Length L Ch R = 1,23841,272,272,272
BEGIN DESCRIPTION:
Deadman 40 51.0
END DESCRIPTION:
XS GIS Cut Line= 3
      1644205.00      6902388.00      1644305.00      6903038.00
      1644355.00      6903237.99
#Sta/Elev= 30
  4342.4 1790.55  4382.9 1788.97  4453.7 1787.06  4494.2 1786.43  4571.3 1784.19
  4625.7 1783.28  4634.5 1782.66  4666.2 1781.90  4702.8 1780.38  4737.0 1780.07
  4834.4 1776.50  4909.0 1775.12  4939.3 1773.68  4949.5 1772.53  4965.9 1771.97
  4995.2 1771.68  4995.5 1771.18  4999.5 1771.18  4999.9 1771.68  5023.2 1771.88
  5051.6 1774.82  5059.3 1776.55  5064.5 1776.73  5082.5 1778.93  5105.7 1780.45
  5113.4 1781.52  5165.0 1783.26  5183.0 1785.06  5188.2 1785.19  5206.2 1786.75
#Mann=3,-1,0
  4342.4    0.05       0  4995.2    0.05       0  4999.9    0.05       0
Bank Sta=4995.2,4999.9
Exp/Cntr=0.3,0.1

Type RM Length L Ch R = 1,23569,126,126,126
BEGIN DESCRIPTION:
Mapping XS 8fcb84b1
END DESCRIPTION:
XS GIS Cut Line= 4
      1644039.55      6902656.31      1644029.17      6902898.45
      1644032.63      6903036.83      1644004.95      6903351.63
#Sta/Elev= 30
  4618.2 1783.33  4649.9 1781.74  4700.0 1781.09  4710.0 1780.65  4720.0 1780.10
  4750.0 1777.27  4780.0 1775.87  4830.1 1774.91  4838.1 1773.82  4843.1 1773.93
  4850.1 1773.00  4889.5 1772.00  4894.5 1772.20  4910.1 1771.49  4967.8 1770.58
  4968.1 1770.08  4972.1 1770.08  4972.5 1770.58  5020.2 1771.54  5027.1 1772.39
  5060.4 1774.09  5080.5 1775.70  5120.6 1777.97  5144.5 1778.53  5170.8 1780.01
  5221.0 1781.45  5231.0 1781.40  5241.1 1782.01  5261.8 1781.92  5315.0 1783.27
#Mann=3,-1,0
  4618.2    0.05       0  4967.8    0.05       0  4972.5    0.05       0
Bank Sta=4967.8,4972.5
Exp/Cntr=0.3,0.1

Type RM Length L Ch R = 1,23443,558,558,558
BEGIN DESCRIPTION:
Deadman 40 50.0
END DESCRIPTION:
XS GIS Cut Line= 3
      1643901.16      6902576.69      1643918.21      6903001.95
      1643915.00      6903490.04
#Sta/Elev= 30
  4574.4 1782.91  4645.8 1780.27  4655.8 1779.67  4665.8 1778.64  4675.8 1778.20
  4745.8 1776.81  4765.9 1776.72  4845.9 1774.89  4916.0 1772.94  4956.0 1770.61
  4973.7 1770.07  4974.0 1769.57  4978.0 1769.57  4978.4 1770.07  5036.0 1770.08
  5046.0 1770.36  5076.0 1772.91  5096.1 1774.14  5116.1 1774.44  5146.1 1775.95
  5196.1 1777.47  5236.1 1778.28  5266.1 1779.47  5286.1 1779.82  5326.1 1781.23
  5356.1 1781.37  5366.1 1781.98  5406.1 1783.17  5456.1 1783.85  5488.1 1784.99
#Mann=3,-1,0
  4574.4    0.05       0  4973.7    0.05       0  4978.4    0.05       0
Bank Sta=4973.7,4978.4
Exp/Cntr=0.3,0.1

Type RM Length L Ch R = 1,22885,445,445,445
BEGIN DESCRIPTION:
Deadman 40 49.0
END DESCRIPTION:
XS GIS Cut Line= 3
      1643455.00      6902787.98      1643405.00      6903138.00
      1643605.01      6903488.01
#Sta/Elev= 30
  4652.3 1781.94  4672.5 1781.52  4682.6 1780.72  4733.1 1779.05  4743.2 1778.35
  4773.5 1777.36  4783.6 1777.51  4915.0 1769.74  4925.1 1769.46  4955.4 1767.51
  4965.5 1766.54  4985.7 1766.17  5000.9 1765.26  5001.3 1764.76  5005.4 1764.76
  5005.7 1765.26  5019.5 1766.14  5028.9 1767.35  5041.1 1767.93  5063.5 1767.54
  5078.6 1766.43  5109.5 1768.12  5116.0 1769.02  5175.0 1771.88  5218.2 1773.33
  5283.0 1776.17  5298.8 1776.38  5342.0 1778.27  5351.4 1778.22  5409.0 1780.54
#Mann=3,-1,0
  4652.3    0.05       0  5000.9    0.05       0  5005.7    0.05       0
Bank Sta=5000.9,5005.7
Exp/Cntr=0.3,0.1

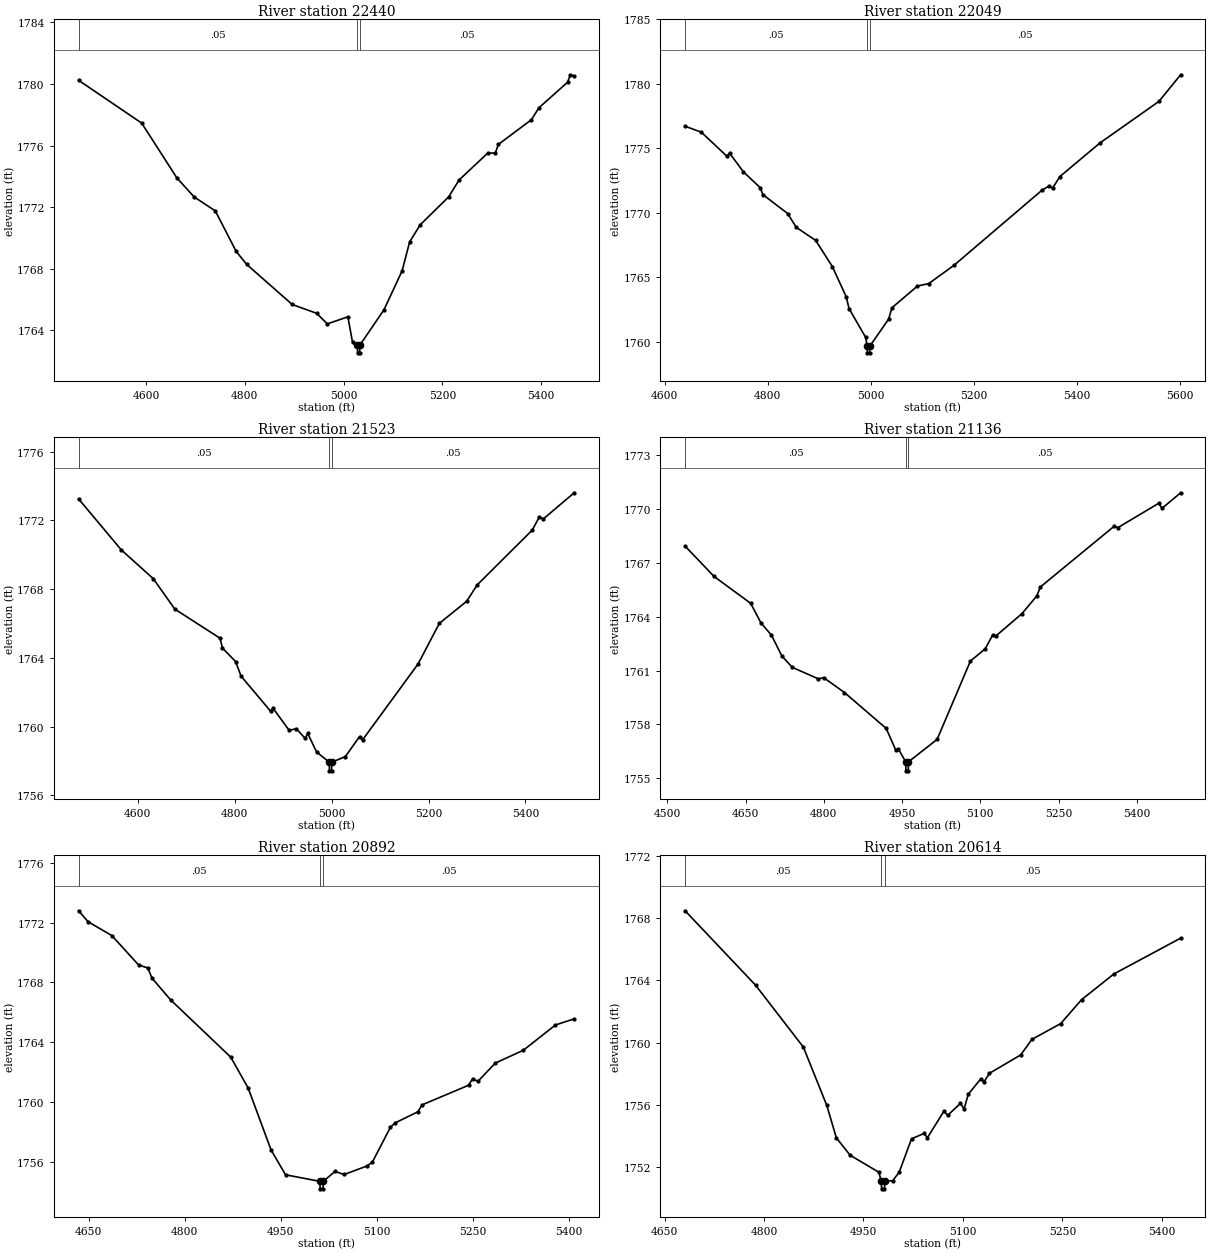
Type RM Length L Ch R = 1,22440,391,391,391
BEGIN DESCRIPTION:
Deadman 40 48.0
END DESCRIPTION:
XS GIS Cut Line= 3
      1642654.97      6902887.97      1643005.00      6903288.00
      1643254.98      6903687.96
#Sta/Elev= 30
  4463.7 1780.24  4591.4 1777.46  4662.6 1773.90  4697.7 1772.66  4740.4 1771.76
  4782.6 1769.13  4804.0 1768.28  4896.1 1765.68  4945.4 1765.11  4967.2 1764.42
  5008.8 1764.88  5018.2 1763.22  5028.1 1763.04  5028.5 1762.54  5032.7 1762.54
  5033.1 1763.04  5081.9 1765.34  5118.5 1767.86  5133.8 1769.74  5155.0 1770.85
  5212.8 1772.67  5234.0 1773.77  5291.8 1775.51  5307.2 1775.52  5313.6 1776.08
  5380.3 1777.68  5395.6 1778.46  5453.4 1780.11  5459.3 1780.60  5466.9 1780.53
#Mann=3,-1,0
  4463.7    0.05       0  5028.1    0.05       0  5033.1    0.05       0
Bank Sta=5028.1,5033.1
Exp/Cntr=0.3,0.1

Type RM Length L Ch R = 1,22049,526,526,526
BEGIN DESCRIPTION:
Deadman 40 47.0
END DESCRIPTION:
XS GIS Cut Line= 3
      1642555.01      6903088.02      1642663.15      6903431.92
      1643055.00      6903888.00
#Sta/Elev= 30
  4639.5 1776.71  4670.9 1776.25  4720.5 1774.39  4725.7 1774.63  4752.8 1773.17
  4785.2 1771.95  4790.5 1771.41  4838.6 1769.94  4855.3 1768.87  4892.9 1767.86
  4925.3 1765.83  4952.4 1763.47  4957.7 1762.57  4990.1 1760.33  4992.8 1759.64
  4993.2 1759.14  4997.5 1759.14  4997.8 1759.64  5034.4 1761.75  5041.1 1762.64
  5090.5 1764.32  5112.4 1764.51  5161.8 1765.94  5331.9 1771.74  5346.2 1772.09
  5352.7 1771.91  5367.0 1772.81  5444.9 1775.42  5559.0 1778.63  5601.3 1780.70
#Mann=3,-1,0
  4639.5    0.05       0  4992.8    0.05       0  4997.8    0.05       0
Bank Sta=4992.8,4997.8
Exp/Cntr=0.3,0.1

Type RM Length L Ch R = 1,21523,387,387,387
BEGIN DESCRIPTION:
Deadman 40 46.0
END DESCRIPTION:
XS GIS Cut Line= 3
      1642405.00      6903188.00      1642255.00      6903688.00
      1642554.99      6904087.99
#Sta/Elev= 30
  4478.4 1773.24  4566.3 1770.28  4632.4 1768.60  4676.8 1766.83  4769.9 1765.14
  4775.1 1764.56  4802.1 1763.78  4813.4 1762.93  4874.3 1760.89  4879.5 1761.06
  4912.5 1759.78  4927.3 1759.87  4945.6 1759.31  4950.8 1759.60  4969.1 1758.52
  4995.3 1757.92  4995.7 1757.42  5000.0 1757.42  5000.4 1757.92  5028.5 1758.25
  5057.7 1759.41  5064.0 1759.22  5178.5 1763.64  5222.3 1766.00  5278.5 1767.28
  5300.4 1768.24  5414.0 1771.43  5428.5 1772.19  5436.9 1772.08  5500.4 1773.60
#Mann=3,-1,0
  4478.4    0.05       0  4995.3    0.05       0  5000.4    0.05       0
Bank Sta=4995.3,5000.4
Exp/Cntr=0.3,0.1

Type RM Length L Ch R = 1,21136,244,244,244
BEGIN DESCRIPTION:
Deadman 40 45.0
END DESCRIPTION:
XS GIS Cut Line= 3
      1641918.76      6903372.43      1641920.18      6903838.43
      1642255.03      6904188.04
#Sta/Elev= 30
  4534.0 1767.93  4589.6 1766.24  4659.6 1764.75  4679.6 1763.65  4699.6 1762.97
  4719.6 1761.81  4739.6 1761.18  4789.6 1760.54  4799.6 1760.61  4839.6 1759.78
  4919.6 1757.78  4938.0 1756.57  4943.0 1756.63  4957.0 1755.92  4957.4 1755.42
  4961.8 1755.42  4962.2 1755.92  5017.2 1757.17  5081.0 1761.53  5109.3 1762.21
  5123.5 1762.97  5130.4 1762.94  5179.8 1764.17  5208.1 1765.15  5215.3 1765.66
  5356.8 1769.04  5363.8 1768.96  5441.7 1770.31  5448.7 1770.04  5484.1 1770.90
#Mann=3,-1,0
  4534.0    0.05       0  4957.0    0.05       0  4962.2    0.05       0
Bank Sta=4957,4962.2
Exp/Cntr=0.3,0.1

Type RM Length L Ch R = 1,20892,278,278,278
BEGIN DESCRIPTION:
Mapping XS e4e36687
END DESCRIPTION:
XS GIS Cut Line= 2
      1641465.53      6903566.15      1641925.67      6904188.90
#Sta/Elev= 30
  4634.0 1772.79  4648.7 1772.06  4685.9 1771.13  4727.6 1769.17  4742.2 1768.96
  4748.5 1768.29  4777.7 1766.83  4871.7 1763.00  4898.8 1760.94  4934.7 1756.79
  4957.3 1755.13  5011.0 1754.69  5011.4 1754.19  5015.8 1754.19  5016.2 1754.69
  5034.5 1755.35  5049.1 1755.15  5084.6 1755.72  5093.0 1755.98  5121.2 1758.31
  5128.5 1758.60  5163.9 1759.34  5170.9 1759.81  5243.3 1761.12  5249.5 1761.55
  5257.9 1761.38  5285.0 1762.60  5328.9 1763.46  5379.0 1765.15  5408.3 1765.56
#Mann=3,-1,0
  4634.0    0.05       0  5011.0    0.05       0  5016.2    0.05       0
Bank Sta=5011,5016.2
Exp/Cntr=0.3,0.1

Type RM Length L Ch R = 1,20614,263,263,263
BEGIN DESCRIPTION:
Deadman 40 44.0
END DESCRIPTION:
XS GIS Cut Line= 3
      1641305.04      6903888.03      1641555.00      6904088.00
      1641954.99      6904238.00
#Sta/Elev= 30
  4681.0 1768.47  4787.4 1763.68  4859.4 1759.70  4894.7 1755.95  4909.1 1753.87
  4929.9 1752.75  4973.1 1751.66  4976.9 1751.09  4977.3 1750.59  4981.7 1750.59
  4982.2 1751.09  4993.9 1751.11  5003.8 1751.65  5022.5 1753.81  5041.2 1754.15
  5046.5 1753.88  5071.4 1755.59  5076.8 1755.31  5096.3 1756.09  5101.7 1755.72
  5107.9 1756.66  5126.6 1757.65  5131.9 1757.48  5140.0 1758.02  5187.1 1759.20
  5204.0 1760.20  5247.6 1761.22  5278.8 1762.75  5327.7 1764.41  5428.3 1766.71
#Mann=3,-1,0
  4681.0    0.05       0  4976.9    0.05       0  4982.2    0.05       0
Bank Sta=4976.9,4982.2
Exp/Cntr=0.3,0.1

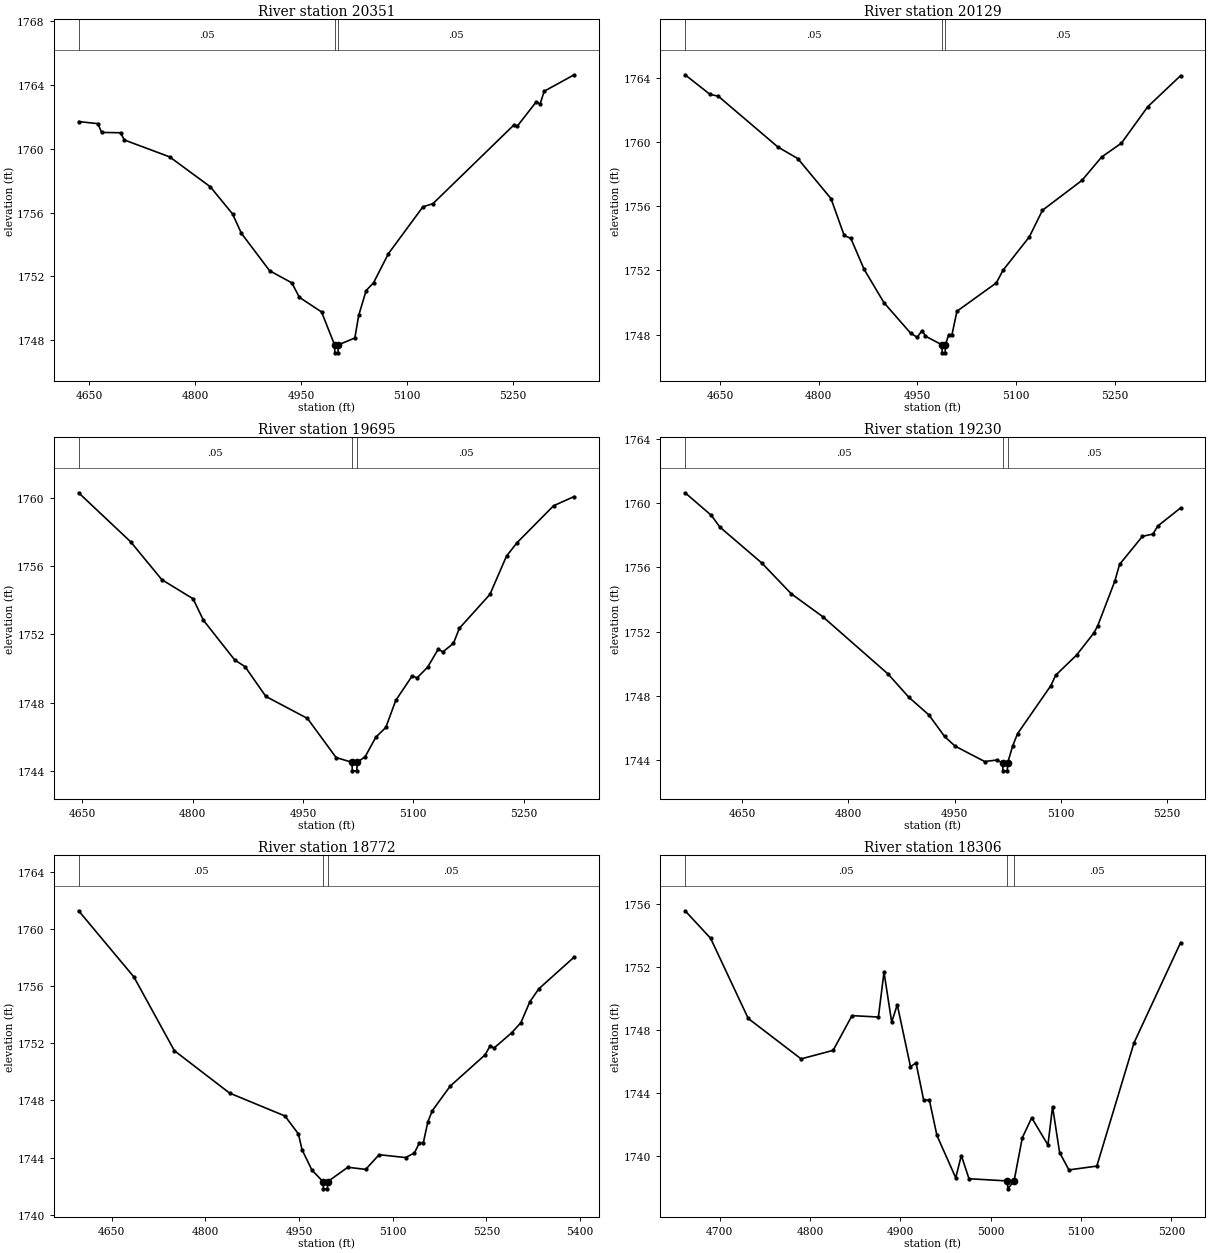
Type RM Length L Ch R = 1,20351,222,222,222
BEGIN DESCRIPTION:
Mapping XS dedda38a
END DESCRIPTION:
XS GIS Cut Line= 2
      1641157.64      6904223.51      1641825.33      6904438.00
#Sta/Elev= 30
  4635.4 1761.70  4662.7 1761.57  4667.9 1761.02  4694.8 1761.00  4700.0 1760.55
  4764.2 1759.49  4821.7 1757.62  4853.2 1755.92  4865.8 1754.70  4905.7 1752.36
  4937.2 1751.60  4947.7 1750.70  4979.2 1749.78  4997.6 1747.72  4998.0 1747.22
  5002.5 1747.22  5002.9 1747.72  5026.3 1748.15  5031.8 1749.57  5042.3 1751.12
  5052.8 1751.61  5073.8 1753.43  5122.6 1756.36  5136.8 1756.56  5251.0 1761.47
  5256.3 1761.42  5283.1 1762.94  5288.4 1762.79  5294.3 1763.60  5336.7 1764.63
#Mann=3,-1,0
  4635.4    0.05       0  4997.6    0.05       0  5002.9    0.05       0
Bank Sta=4997.6,5002.9
Exp/Cntr=0.3,0.1

Type RM Length L Ch R = 1,20129,434,434,434
BEGIN DESCRIPTION:
Deadman 40 43.0
END DESCRIPTION:
XS GIS Cut Line= 3
      1641055.04      6904488.00      1641455.00      6904538.00
      1641805.03      6904538.00
#Sta/Elev= 30
  4597.1 1764.18  4634.9 1762.96  4647.4 1762.85  4738.2 1759.68  4768.4 1758.96
  4818.8 1756.47  4838.9 1754.17  4849.0 1753.99  4869.2 1752.06  4899.4 1749.98
  4939.7 1748.09  4949.8 1747.83  4957.3 1748.25  4962.4 1747.90  4987.4 1747.36
  4987.8 1746.86  4992.3 1746.86  4992.7 1747.36  4997.7 1747.99  5002.7 1747.99
  5010.2 1749.45  5070.2 1751.22  5080.2 1752.00  5120.2 1754.08  5140.2 1755.74
  5200.2 1757.60  5230.2 1759.06  5260.2 1759.92  5300.2 1762.19  5350.2 1764.13
#Mann=3,-1,0
  4597.1    0.05       0  4987.4    0.05       0  4992.7    0.05       0
Bank Sta=4987.4,4992.7
Exp/Cntr=0.3,0.1

Type RM Length L Ch R = 1,19695,465,465,465
BEGIN DESCRIPTION:
Deadman 40 42.0
END DESCRIPTION:
XS GIS Cut Line= 3
      1641105.01      6904688.01      1641355.00      6904938.00
      1641555.00      6905188.00
#Sta/Elev= 30
  4645.0 1760.29  4715.7 1757.42  4758.1 1755.20  4800.6 1754.08  4814.7 1752.82
  4857.1 1750.50  4871.3 1750.10  4899.5 1748.36  4956.1 1747.07  4995.0 1744.78
  5016.6 1744.50  5017.1 1744.00  5023.2 1744.00  5023.7 1744.50  5034.6 1744.83
  5049.0 1745.97  5062.6 1746.54  5076.2 1748.13  5098.6 1749.57  5105.0 1749.44
  5119.4 1750.07  5133.8 1751.12  5140.2 1750.97  5154.6 1751.47  5162.6 1752.35
  5204.2 1754.34  5226.7 1756.58  5241.1 1757.37  5290.7 1759.53  5318.7 1760.07
#Mann=3,-1,0
  4645.0    0.05       0  5016.6    0.05       0  5023.7    0.05       0
Bank Sta=5016.6,5023.7
Exp/Cntr=0.3,0.1

Type RM Length L Ch R = 1,19230,458,458,458
BEGIN DESCRIPTION:
Deadman 40 41.0
END DESCRIPTION:
XS GIS Cut Line= 3
      1640754.99      6905037.99      1641105.00      6905288.00
      1641355.01      6905388.00
#Sta/Elev= 30
  4569.5 1760.64  4606.4 1759.24  4618.7 1758.50  4677.7 1756.27  4719.4 1754.35
  4763.7 1752.93  4855.9 1749.36  4885.3 1747.91  4913.6 1746.81  4935.7 1745.47
  4950.5 1744.87  4992.3 1743.91  5009.1 1744.00  5017.6 1743.83  5018.1 1743.33
  5024.3 1743.33  5024.8 1743.83  5031.9 1744.89  5038.7 1745.64  5085.8 1748.64
  5092.5 1749.28  5122.1 1750.54  5146.4 1751.91  5151.8 1752.35  5176.0 1755.14
  5182.7 1756.18  5215.0 1757.93  5229.8 1758.07  5236.6 1758.57  5268.9 1759.70
#Mann=3,-1,0
  4569.5    0.05       0  5017.6    0.03       0  5024.8    0.05       0
Bank Sta=5017.6,5024.8
Exp/Cntr=0.3,0.1

Type RM Length L Ch R = 1,18772,466,466,466
BEGIN DESCRIPTION:
Deadman 40 40.0
END DESCRIPTION:
XS GIS Cut Line= 3
      1640505.04      6905438.02      1640855.00      6905638.00
      1641155.02      6905888.01
#Sta/Elev= 30
  4597.1 1761.27  4685.6 1756.64  4750.4 1751.48  4838.9 1748.51  4927.5 1746.91
  4949.1 1745.65  4954.8 1744.56  4970.7 1743.12  4988.6 1742.31  4989.1 1741.81
  4995.4 1741.81  4995.9 1742.31  5028.2 1743.32  5056.8 1743.17  5078.3 1744.20
  5120.6 1744.00  5134.9 1744.32  5142.7 1745.02  5149.2 1745.05  5156.4 1746.50
  5163.5 1747.28  5192.2 1749.00  5248.1 1751.19  5256.0 1751.81  5262.5 1751.67
  5291.1 1752.75  5305.4 1753.44  5319.7 1754.90  5334.1 1755.81  5390.7 1758.03
#Mann=3,-1,0
  4597.1    0.05       0  4988.6    0.05       0  4995.9    0.05       0
Bank Sta=4988.6,4995.9
Exp/Cntr=0.3,0.1

Type RM Length L Ch R = 1,18306,262,262,262
BEGIN DESCRIPTION:
Deadman 40 39.0
END DESCRIPTION:
XS GIS Cut Line= 3
      1640451.66      6905762.48      1640655.00      6906038.00
      1640855.02      6906088.00
#Sta/Elev= 30
  4661.6 1755.55  4689.8 1753.81  4731.5 1748.73  4790.0 1746.17  4825.5 1746.71
  4846.4 1748.91  4875.6 1748.82  4881.8 1751.67  4890.3 1748.50  4896.5 1749.60
  4911.1 1745.68  4917.3 1745.91  4925.7 1743.56  4932.0 1743.57  4940.4 1741.32
  4961.2 1738.64  4967.4 1740.05  4975.9 1738.58  5018.4 1738.44  5018.9 1737.94
  5025.8 1738.44  5034.9 1741.17  5045.3 1742.44  5063.3 1740.72  5068.4 1743.14
  5076.2 1740.24  5086.5 1739.14  5117.4 1739.38  5158.6 1747.19  5210.2 1753.54
#Mann=3,-1,0
  4661.6    0.05       0  5018.4    0.03       0  5025.8    0.05       0
Bank Sta=5018.4,5025.8
Exp/Cntr=0.3,0.1

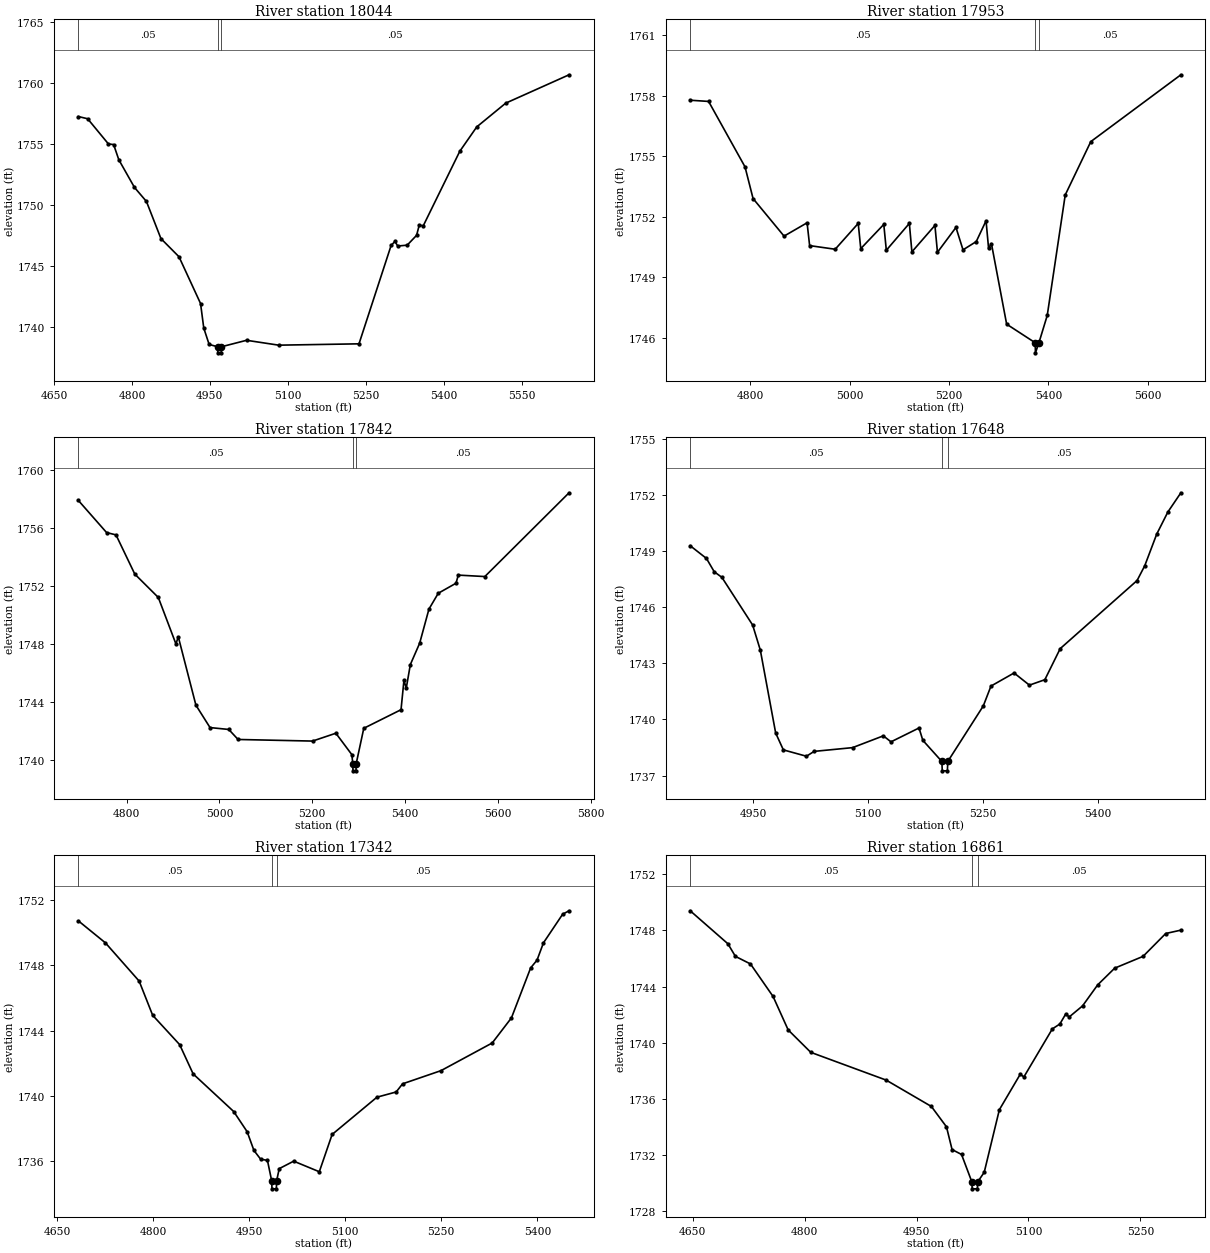
Type RM Length L Ch R = 1,18044,91,91,91
BEGIN DESCRIPTION:
Mapping XS be1f22f3
END DESCRIPTION:
XS GIS Cut Line= 3
      1640357.92      6905790.26      1640364.87      6905918.75
      1640559.32      6906710.45
#Sta/Elev= 30
  4697.1 1757.27  4714.9 1757.09  4754.9 1755.02  4764.9 1754.97  4774.9 1753.72
  4805.0 1751.45  4828.0 1750.30  4855.9 1747.25  4890.6 1745.76  4932.1 1741.92
  4938.3 1739.90  4948.6 1738.56  4964.8 1738.37  4965.3 1737.87  4971.8 1737.87
  4972.3 1738.37  5020.6 1738.90  5082.4 1738.50  5236.9 1738.61  5298.7 1746.69
  5306.1 1747.02  5311.3 1746.64  5329.6 1746.71  5347.7 1747.52  5352.8 1748.36
  5360.5 1748.30  5430.8 1754.42  5463.4 1756.42  5519.1 1758.37  5641.0 1760.70
#Mann=3,-1,0
  4697.1    0.05       0  4964.8    0.03       0  4972.3    0.05       0
Bank Sta=4964.8,4972.3
Exp/Cntr=0.3,0.1

Type RM Length L Ch R = 1,17953,111,111,111
BEGIN DESCRIPTION:
Mapping XS 61e47dae
END DESCRIPTION:
XS GIS Cut Line= 3
      1640319.74      6905776.37      1640281.54      6905911.81
      1640444.74      6906741.69
#Sta/Elev= 30
  4679.7 1757.77  4716.7 1757.71  4789.9 1754.47  4806.1 1752.90  4868.4 1751.04
  4914.7 1751.70  4919.8 1750.57  4971.2 1750.39  5017.5 1751.67  5022.6 1750.42
  5068.9 1751.62  5074.0 1750.34  5120.3 1751.67  5125.4 1750.26  5171.7 1751.57
  5176.8 1750.24  5214.0 1751.47  5228.2 1750.36  5254.8 1750.77  5274.5 1751.80
  5279.6 1750.43  5285.3 1750.67  5315.9 1746.68  5373.3 1745.76  5373.8 1745.26
  5380.8 1745.76  5397.5 1747.11  5433.7 1753.08  5485.1 1755.72  5666.2 1759.03
#Mann=3,-1,0
  4679.7    0.05       0  5373.3    0.03       0  5380.8    0.05       0
Bank Sta=5373.3,5380.8
Exp/Cntr=0.3,0.1

Type RM Length L Ch R = 1,17842,194,194,194
BEGIN DESCRIPTION:
Deadman 40 38.0
END DESCRIPTION:
XS GIS Cut Line= 3
      1640254.99      6905788.03      1640205.00      6906088.00
      1640271.12      6906838.89
#Sta/Elev= 30
  4695.8 1757.90  4756.6 1755.69  4776.9 1755.53  4817.4 1752.83  4868.1 1751.22
  4906.1 1748.02  4911.2 1748.51  4949.2 1743.80  4979.6 1742.26  5020.0 1742.13
  5040.1 1741.44  5200.7 1741.33  5250.9 1741.87  5285.5 1740.39  5287.3 1739.78
  5287.8 1739.28  5294.3 1739.28  5294.8 1739.78  5311.1 1742.21  5391.4 1743.49
  5397.7 1745.51  5402.7 1744.98  5411.5 1746.60  5431.6 1748.07  5451.6 1750.42
  5471.7 1751.51  5509.9 1752.20  5514.9 1752.76  5572.1 1752.66  5753.7 1758.43
#Mann=3,-1,0
  4695.8    0.05       0  5287.3    0.03       0  5294.8    0.05       0
Bank Sta=5287.3,5294.8
Exp/Cntr=0.3,0.1

Type RM Length L Ch R = 1,17648,306,306,306
BEGIN DESCRIPTION:
Mapping XS e76e99fc
END DESCRIPTION:
XS GIS Cut Line= 2
      1640019.39      6905956.81      1639978.00      6906594.97
#Sta/Elev= 30
  4868.3 1749.28  4889.5 1748.60  4899.6 1747.89  4909.6 1747.59  4949.7 1745.04
  4959.7 1743.70  4979.7 1739.27  4989.7 1738.37  5019.8 1738.03  5029.8 1738.29
  5079.9 1738.49  5120.0 1739.12  5130.0 1738.80  5166.5 1739.54  5171.5 1738.88
  5196.3 1737.75  5196.8 1737.25  5203.5 1737.25  5204.0 1737.75  5250.3 1740.72
  5260.3 1741.78  5290.4 1742.48  5310.4 1741.83  5330.5 1742.12  5350.5 1743.78
  5450.7 1747.42  5460.7 1748.21  5476.3 1749.90  5490.8 1751.08  5507.8 1752.11
#Mann=3,-1,0
  4868.3    0.05       0  5196.3    0.03       0  5204.0    0.05       0
Bank Sta=5196.3,5204
Exp/Cntr=0.3,0.1

Type RM Length L Ch R = 1,17342,481,481,481
BEGIN DESCRIPTION:
Deadman 40 37.0
END DESCRIPTION:
XS GIS Cut Line= 3
      1639605.00      6905787.99      1639705.00      6906088.00
      1639705.00      6906537.96
#Sta/Elev= 30
  4683.3 1750.74  4725.5 1749.39  4778.2 1747.04  4799.3 1744.94  4841.4 1743.14
  4862.5 1741.34  4925.8 1739.03  4946.8 1737.79  4957.4 1736.64  4967.9 1736.10
  4978.5 1736.03  4985.1 1734.78  4985.6 1734.28  4992.4 1734.28  4992.9 1734.78
  4996.9 1735.52  5019.5 1735.98  5059.5 1735.33  5079.5 1737.62  5149.5 1739.91
  5179.5 1740.23  5189.5 1740.73  5249.5 1741.54  5329.5 1743.24  5359.5 1744.78
  5389.5 1747.85  5399.5 1748.33  5409.5 1749.39  5439.5 1751.15  5449.5 1751.36
#Mann=3,-1,0
  4683.3    0.05       0  4985.1    0.05       0  4992.9    0.05       0
Bank Sta=4985.1,4992.9
Exp/Cntr=0.3,0.1

Type RM Length L Ch R = 1,16861,468,468,468
BEGIN DESCRIPTION:
Deadman 40 36.0
END DESCRIPTION:
XS GIS Cut Line= 3
      1639305.00      6905837.99      1639255.00      6906188.00
      1639305.00      6906487.99
#Sta/Elev= 30
  4646.6 1749.40  4697.1 1747.05  4707.2 1746.15  4727.4 1745.61  4757.7 1743.29
  4777.9 1740.91  4808.2 1739.31  4909.3 1737.33  4969.9 1735.45  4990.1 1734.00
  4997.6 1732.38  5010.3 1732.03  5024.1 1730.08  5024.6 1729.58  5031.5 1729.58
  5032.0 1730.08  5040.7 1730.76  5061.0 1735.22  5088.9 1737.74  5093.9 1737.56
  5132.0 1740.98  5142.1 1741.33  5149.7 1742.02  5154.8 1741.84  5172.5 1742.62
  5192.8 1744.12  5215.6 1745.31  5253.6 1746.15  5284.0 1747.78  5304.3 1748.02
#Mann=3,-1,0
  4646.6    0.05       0  5024.1    0.05       0  5032.0    0.05       0
Bank Sta=5024.1,5032
Exp/Cntr=0.3,0.1