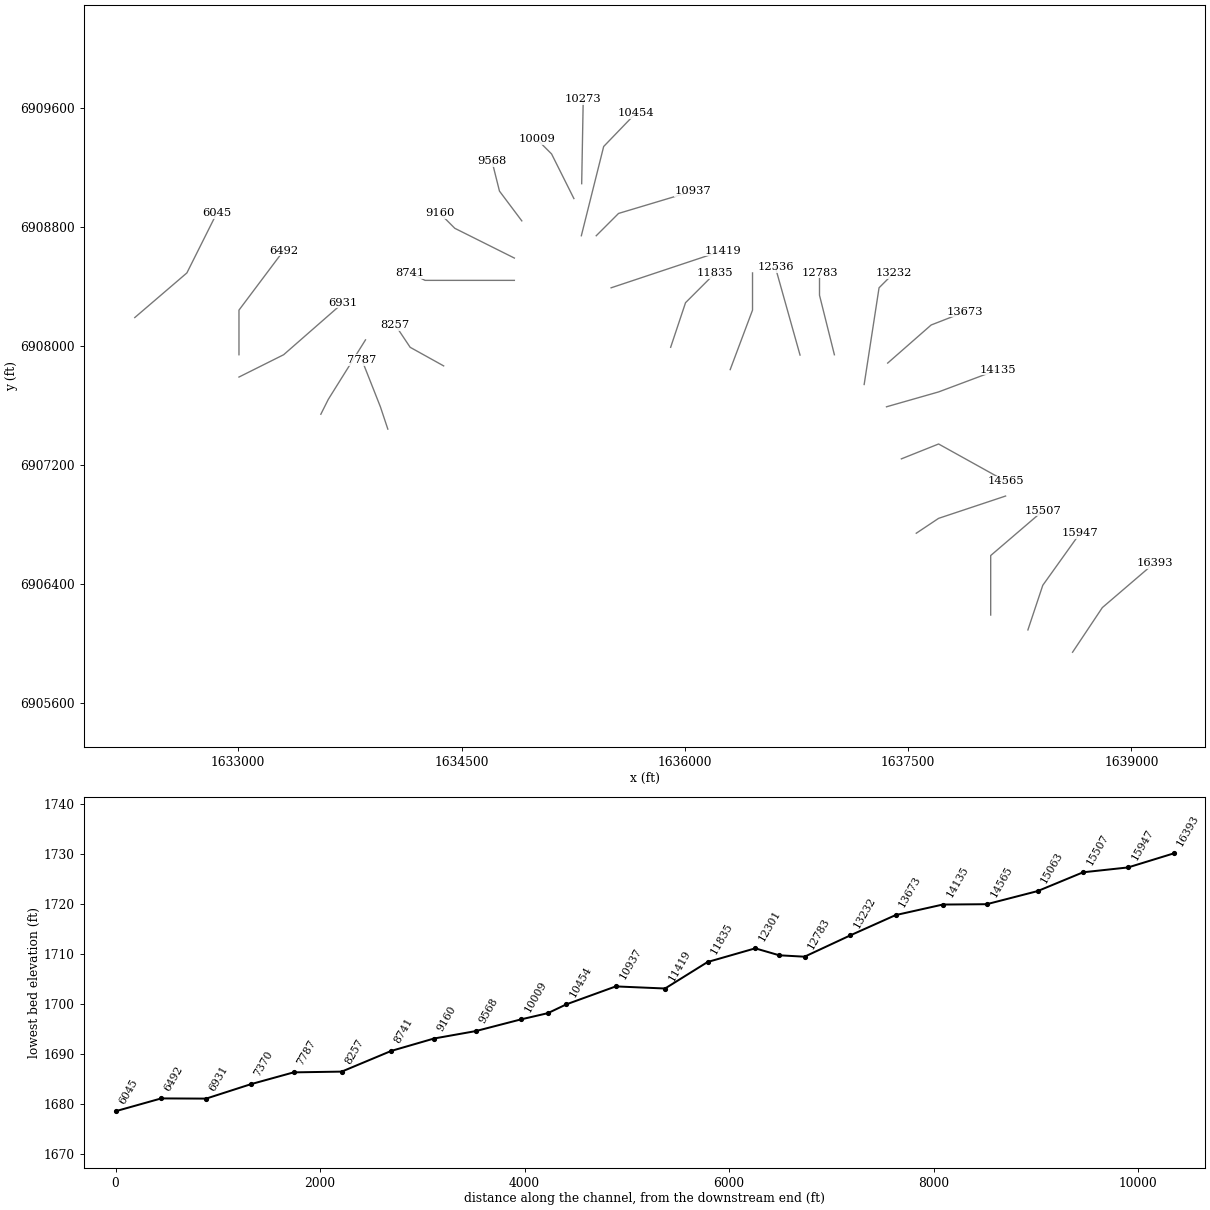
HEC-RAS study Deadman 40.prj: Deadman 40 Base Level Engineering

--- Deadman 40.g01 (geometry) --- (continued)

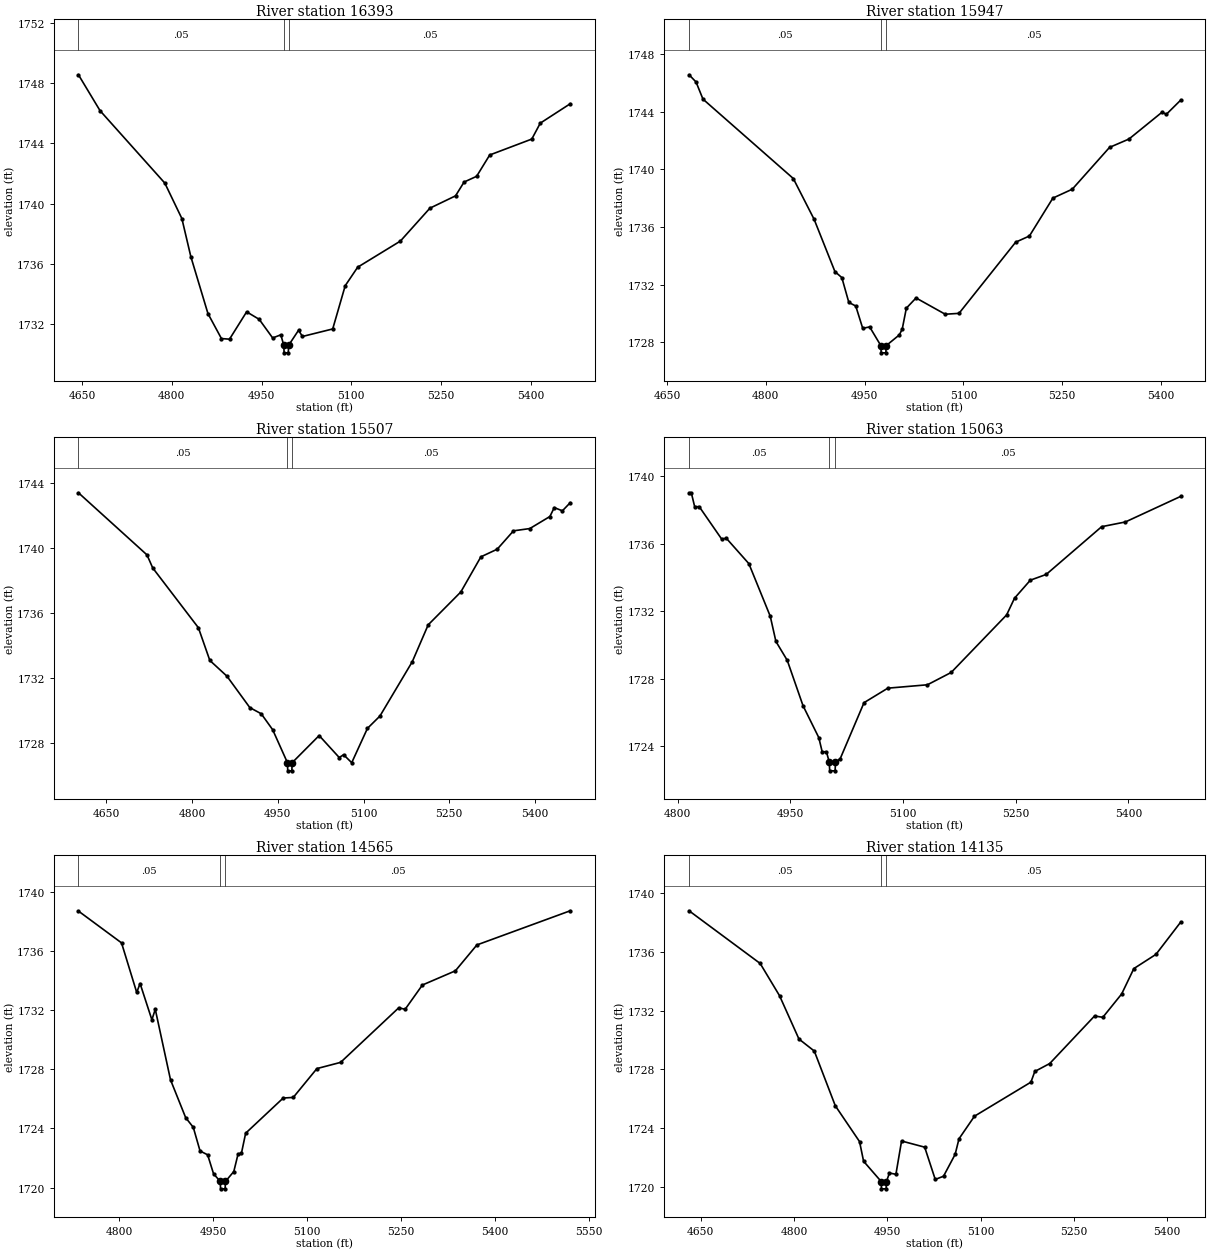
Type RM Length L Ch R = 1,16393,446,446,446
BEGIN DESCRIPTION:
Deadman 40 35.0
END DESCRIPTION:
XS GIS Cut Line= 3
      1638604.98      6905937.97      1638805.00      6906238.00
      1639155.02      6906538.02
#Sta/Elev= 30
  4644.1 1748.57  4680.2 1746.18  4788.4 1741.36  4816.9 1739.00  4831.9 1736.46
  4860.5 1732.67  4883.0 1731.01  4896.5 1730.97  4925.1 1732.79  4946.1 1732.29
  4968.6 1731.05  4982.2 1731.26  4987.2 1730.56  4987.7 1730.06  4994.7 1730.06
  4995.2 1730.56  5011.8 1731.56  5018.4 1731.15  5068.9 1731.65  5089.8 1734.53
  5110.6 1735.76  5182.0 1737.50  5231.3 1739.69  5274.1 1740.51  5288.4 1741.43
  5309.3 1741.81  5331.2 1743.23  5401.5 1744.29  5415.7 1745.35  5465.7 1746.64
#Mann=3,-1,0
  4644.1    0.05       0  4987.2    0.03       0  4995.2    0.05       0
Bank Sta=4987.2,4995.2
Exp/Cntr=0.3,0.1

Type RM Length L Ch R = 1,15947,440,440,440
BEGIN DESCRIPTION:
Deadman 40 34.0
END DESCRIPTION:
XS GIS Cut Line= 3
      1638304.99      6906087.96      1638405.00      6906388.00
      1638655.01      6906738.01
#Sta/Elev= 30
  4683.6 1746.56  4694.2 1746.06  4704.7 1744.87  4841.8 1739.36  4873.4 1736.53
  4905.0 1732.90  4915.5 1732.48  4926.1 1730.76  4936.6 1730.51  4947.2 1728.96
  4957.7 1729.06  4974.7 1727.76  4975.2 1727.26  4982.3 1727.26  4982.8 1727.76
  5002.9 1728.51  5007.2 1728.92  5013.4 1730.36  5028.1 1731.07  5072.4 1729.94
  5093.3 1730.00  5179.3 1734.94  5200.2 1735.37  5235.8 1738.00  5265.3 1738.62
  5321.8 1741.52  5351.3 1742.10  5401.7 1743.97  5407.9 1743.81  5430.0 1744.81
#Mann=3,-1,0
  4683.6    0.05       0  4974.7    0.03       0  4982.8    0.05       0
Bank Sta=4974.7,4982.8
Exp/Cntr=0.3,0.1

Type RM Length L Ch R = 1,15507,444,444,444
BEGIN DESCRIPTION:
Deadman 40 33.0
END DESCRIPTION:
XS GIS Cut Line= 3
      1638055.00      6906188.03      1638055.00      6906588.00
      1638404.97      6906887.97
#Sta/Elev= 30
  4600.9 1743.39  4720.9 1739.57  4730.9 1738.77  4810.9 1735.09  4830.9 1733.08
  4860.9 1732.11  4900.9 1730.18  4920.9 1729.80  4940.9 1728.82  4966.8 1726.79
  4967.3 1726.29  4974.5 1726.29  4975.0 1726.79  5022.3 1728.46  5057.4 1727.11
  5065.1 1727.28  5079.3 1726.79  5106.8 1728.90  5128.7 1729.66  5185.3 1733.00
  5213.2 1735.27  5270.3 1737.29  5305.4 1739.45  5334.0 1739.92  5362.5 1741.05
  5391.1 1741.19  5426.2 1741.93  5433.9 1742.48  5448.1 1742.28  5461.8 1742.78
#Mann=3,-1,0
  4600.9    0.05       0  4966.8    0.03       0  4975.0    0.05       0
Bank Sta=4966.8,4975
Exp/Cntr=0.3,0.1

Type RM Length L Ch R = 1,15063,498,498,498
BEGIN DESCRIPTION:
Deadman 40 32.0
END DESCRIPTION:
XS GIS Cut Line= 3
      1637555.04      6906738.03      1637705.00      6906838.00
      1638155.03      6906988.01
#Sta/Elev= 30
  4815.2 1739.02  4818.2 1739.02  4822.7 1738.19  4828.7 1738.20  4858.7 1736.27
  4864.7 1736.33  4894.8 1734.82  4923.3 1731.70  4930.8 1730.21  4945.9 1729.09
  4966.9 1726.40  4987.9 1724.51  4992.4 1723.67  4998.1 1723.67  5001.9 1723.04
  5002.4 1722.54  5009.6 1722.54  5010.1 1723.04  5016.5 1723.27  5048.1 1726.58
  5079.8 1727.44  5132.5 1727.64  5164.1 1728.37  5237.9 1731.78  5248.4 1732.77
  5269.5 1733.84  5290.6 1734.18  5364.4 1737.01  5396.0 1737.29  5469.8 1738.81
#Mann=3,-1,0
  4815.2    0.05       0  5001.9    0.05       0  5010.1    0.05       0
Bank Sta=5001.9,5010.1
Exp/Cntr=0.3,0.1

Type RM Length L Ch R = 1,14565,430,430,430
BEGIN DESCRIPTION:
Deadman 40 31.0
END DESCRIPTION:
XS GIS Cut Line= 3
      1637454.98      6907237.99      1637705.00      6907338.00
      1638155.04      6907087.98
#Sta/Elev= 30
  4735.4 1738.70  4804.1 1736.55  4828.3 1733.20  4833.7 1733.80  4852.5 1731.35
  4857.9 1732.06  4882.2 1727.29  4906.4 1724.73  4918.5 1724.08  4929.3 1722.48
  4941.4 1722.22  4950.8 1720.94  4961.5 1720.42  4962.0 1719.92  4969.3 1719.92
  4969.8 1720.42  4983.1 1721.09  4989.9 1722.27  4995.3 1722.33  5002.0 1723.68
  5061.9 1726.06  5077.9 1726.10  5115.6 1728.05  5153.4 1728.47  5246.1 1732.16
  5256.3 1732.06  5283.8 1733.70  5336.4 1734.66  5370.7 1736.41  5519.5 1738.72
#Mann=3,-1,0
  4735.4    0.05       0  4961.5    0.03       0  4969.8    0.05       0
Bank Sta=4961.5,4969.8
Exp/Cntr=0.3,0.1

Type RM Length L Ch R = 1,14135,462,462,462
BEGIN DESCRIPTION:
Deadman 40 30.0
END DESCRIPTION:
XS GIS Cut Line= 3
      1637354.99      6907588.00      1637705.00      6907688.00
      1638104.99      6907838.00
#Sta/Elev= 30
  4631.0 1738.80  4745.4 1735.21  4776.6 1733.01  4807.8 1730.06  4832.5 1729.24
  4866.3 1725.51  4905.3 1723.07  4911.8 1721.73  4940.1 1720.35  4940.6 1719.85
  4948.1 1719.85  4948.6 1720.35  4953.4 1720.93  4963.8 1720.84  4972.9 1723.11
  5010.1 1722.69  5027.1 1720.49  5040.4 1720.71  5059.1 1722.20  5065.3 1723.26
  5090.2 1724.80  5181.0 1727.12  5187.3 1727.85  5211.3 1728.39  5283.4 1731.63
  5296.7 1731.54  5327.0 1733.13  5346.6 1734.86  5382.2 1735.83  5422.2 1738.04
#Mann=3,-1,0
  4631.0    0.05       0  4940.1    0.03       0  4948.6    0.05       0
Bank Sta=4940.1,4948.6
Exp/Cntr=0.3,0.1

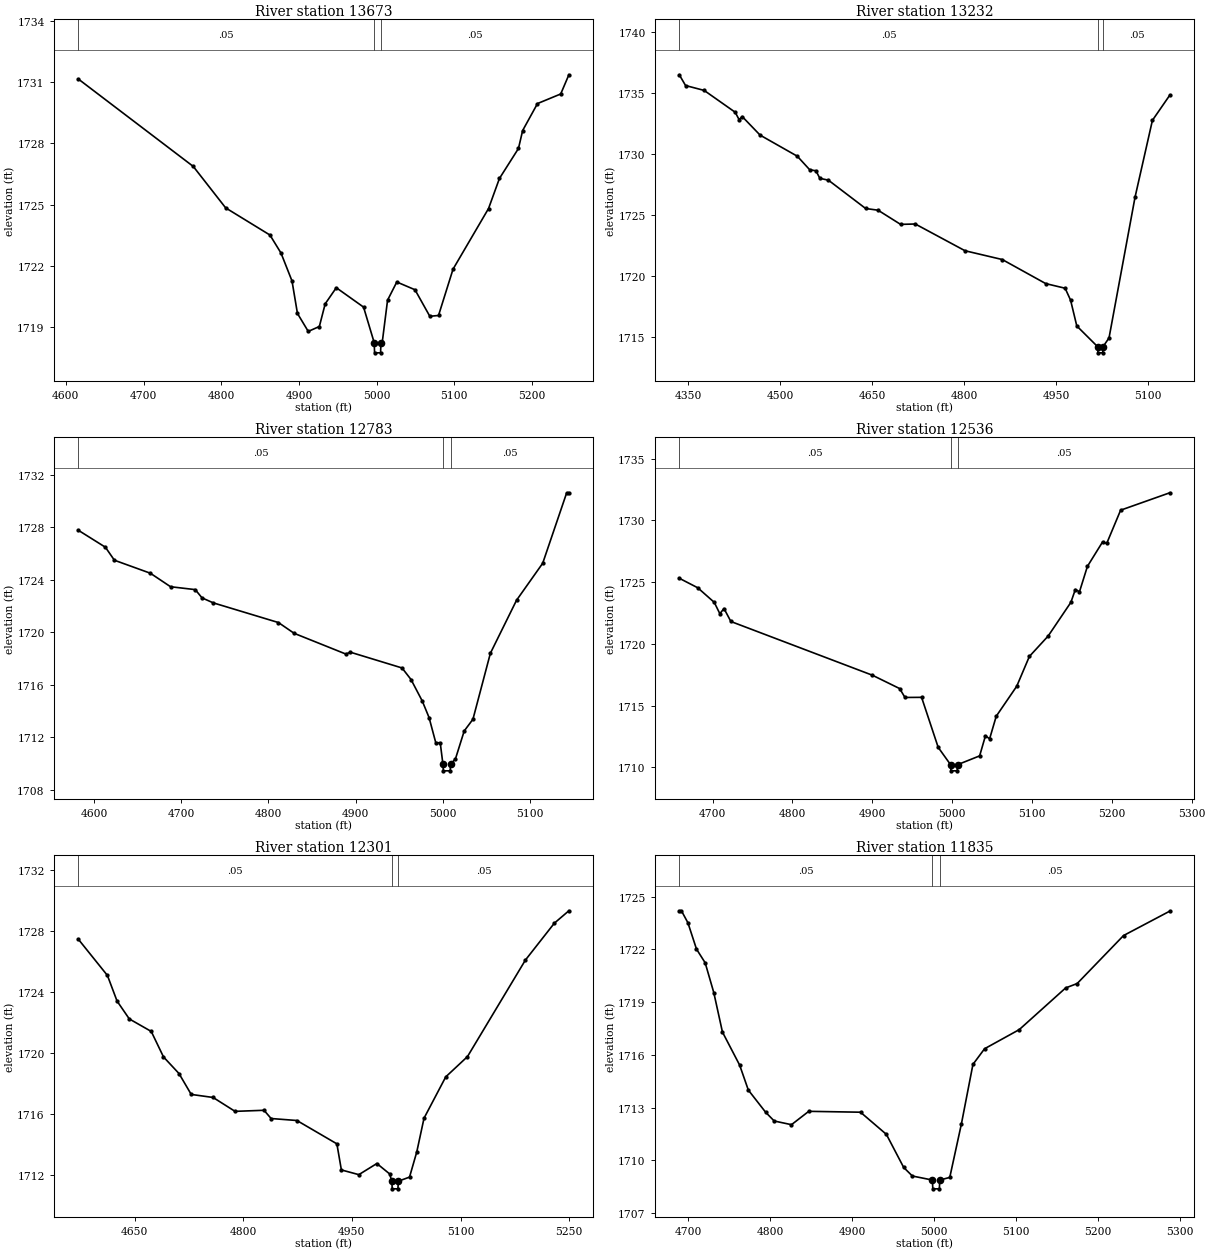
Type RM Length L Ch R = 1,13673,441,441,441
BEGIN DESCRIPTION:
Deadman 40 29.0
END DESCRIPTION:
XS GIS Cut Line= 3
      1637362.95      6907881.87      1637655.00      6908138.00
      1637881.37      6908226.21
#Sta/Elev= 30
  4616.1 1731.15  4764.0 1726.87  4805.7 1724.84  4862.7 1723.51  4876.9 1722.63
  4891.1 1721.26  4898.1 1719.67  4912.0 1718.79  4926.3 1719.03  4933.8 1720.14
  4948.1 1720.93  4983.2 1719.98  4996.9 1718.24  4997.4 1717.74  5005.1 1717.74
  5005.6 1718.24  5007.2 1718.24  5014.1 1720.32  5026.0 1721.21  5049.4 1720.83
  5068.5 1719.53  5079.7 1719.57  5098.4 1721.84  5144.1 1724.81  5158.1 1726.28
  5182.6 1727.75  5188.0 1728.63  5207.1 1729.95  5237.0 1730.42  5247.5 1731.36
#Mann=3,-1,0
  4616.1    0.05       0  4996.9    0.03       0  5005.6    0.05       0
Bank Sta=4996.9,5005.6
Exp/Cntr=0.3,0.1

Type RM Length L Ch R = 1,13232,449,449,449
BEGIN DESCRIPTION:
Deadman 40 28.0
END DESCRIPTION:
XS GIS Cut Line= 3
      1637204.99      6907737.95      1637305.00      6908388.00
      1637404.99      6908487.99
#Sta/Elev= 30
  4335.8 1736.48  4346.0 1735.60  4376.3 1735.20  4426.9 1733.41  4433.2 1732.81
  4438.3 1733.06  4467.4 1731.54  4528.1 1729.81  4548.3 1728.70  4558.4 1728.62
  4564.8 1728.00  4578.7 1727.85  4639.4 1725.53  4659.6 1725.39  4696.3 1724.23
  4720.3 1724.26  4801.3 1722.07  4862.0 1721.35  4932.8 1719.38  4964.4 1719.00
  4973.3 1718.02  4983.4 1715.91  5017.4 1714.21  5017.9 1713.71  5025.6 1713.71
  5026.1 1714.21  5035.9 1714.93  5078.3 1726.46  5106.6 1732.75  5134.9 1734.81
#Mann=3,-1,0
  4335.8    0.05       0  5017.4    0.05       0  5026.1    0.05       0
Bank Sta=5017.4,5026.1
Exp/Cntr=0.3,0.1

Type RM Length L Ch R = 1,12783,247,247,247
BEGIN DESCRIPTION:
Deadman 40 27.0
END DESCRIPTION:
XS GIS Cut Line= 3
      1637005.01      6907937.95      1636905.00      6908338.00
      1636905.00      6908488.04
#Sta/Elev= 30
  4582.1 1727.77  4613.1 1726.48  4623.4 1725.49  4664.6 1724.50  4687.8 1723.47
  4716.1 1723.25  4723.9 1722.62  4736.8 1722.24  4811.5 1720.74  4829.5 1719.92
  4888.8 1718.34  4894.0 1718.48  4953.2 1717.28  4963.5 1716.40  4976.4 1714.76
  4984.2 1713.50  4991.9 1711.58  4997.0 1711.58  5000.1 1709.94  5000.6 1709.44
  5008.4 1709.44  5008.9 1709.94  5014.5 1710.36  5024.5 1712.48  5034.5 1713.37
  5054.5 1718.40  5084.5 1722.44  5114.5 1725.26  5142.0 1730.63  5144.5 1730.63
#Mann=3,-1,0
  4582.1    0.05       0  5000.1    0.05       0  5008.9    0.05       0
Bank Sta=5000.1,5008.9
Exp/Cntr=0.3,0.1

Type RM Length L Ch R = 1,12536,235,235,235
BEGIN DESCRIPTION:
Mapping XS 83df9465
END DESCRIPTION:
XS GIS Cut Line= 2
      1636774.19      6907935.79      1636608.15      6908527.33
#Sta/Elev= 30
  4658.2 1725.31  4681.3 1724.54  4702.0 1723.36  4709.0 1722.44  4714.2 1722.86
  4722.8 1721.81  4900.1 1717.46  4934.2 1716.38  4940.9 1715.66  4961.7 1715.67
  4982.5 1711.62  4998.0 1710.22  4998.5 1709.72  5006.3 1709.72  5006.8 1710.22
  5034.4 1710.93  5041.7 1712.56  5046.9 1712.31  5055.2 1714.14  5080.9 1716.57
  5096.7 1718.98  5120.2 1720.63  5148.7 1723.36  5154.3 1724.40  5159.5 1724.22
  5169.4 1726.27  5188.4 1728.25  5193.6 1728.13  5211.0 1730.82  5272.6 1732.23
#Mann=3,-1,0
  4658.2    0.05       0  4998.0    0.05       0  5006.8    0.05       0
Bank Sta=4998,5006.8
Exp/Cntr=0.3,0.1

Type RM Length L Ch R = 1,12301,466,466,466
BEGIN DESCRIPTION:
Deadman 40 26.0
END DESCRIPTION:
XS GIS Cut Line= 3
      1636304.99      6907837.98      1636455.00      6908238.00
      1636455.00      6908487.97
#Sta/Elev= 30
  4572.4 1727.47  4612.5 1725.10  4625.8 1723.42  4642.7 1722.25  4673.0 1721.43
  4689.9 1719.76  4711.3 1718.67  4728.2 1717.30  4758.4 1717.10  4788.7 1716.19
  4828.7 1716.26  4838.5 1715.72  4874.1 1715.59  4929.3 1714.06  4935.5 1712.35
  4959.6 1712.04  4984.5 1712.77  5002.1 1712.09  5005.2 1711.61  5005.7 1711.11
  5013.6 1711.11  5014.1 1711.61  5029.6 1711.88  5039.6 1713.53  5049.6 1715.74
  5079.6 1718.45  5109.6 1719.78  5189.6 1726.11  5229.6 1728.53  5249.6 1729.34
#Mann=3,-1,0
  4572.4    0.05       0  5005.2    0.05       0  5014.1    0.05       0
Bank Sta=5005.2,5014.1
Exp/Cntr=0.3,0.1

Type RM Length L Ch R = 1,11835,416,416,416
BEGIN DESCRIPTION:
Deadman 40 25.0
END DESCRIPTION:
XS GIS Cut Line= 3
      1635905.01      6907988.03      1636005.00      6908288.00
      1636204.98      6908487.98
#Sta/Elev= 30
  4689.0 1724.20  4691.6 1724.20  4699.5 1723.52  4710.0 1722.02  4720.6 1721.24
  4731.1 1719.55  4741.7 1717.30  4762.7 1715.42  4773.3 1714.00  4794.4 1712.74
  4804.9 1712.24  4826.0 1712.03  4847.1 1712.79  4910.3 1712.74  4941.9 1711.48
  4963.0 1709.60  4973.6 1709.11  4998.1 1708.88  4998.6 1708.38  5006.6 1708.38
  5007.1 1708.88  5019.3 1709.03  5033.5 1712.07  5047.6 1715.46  5061.8 1716.35
  5104.2 1717.44  5160.8 1719.81  5174.9 1720.06  5231.5 1722.79  5288.0 1724.18
#Mann=3,-1,0
  4689.0    0.05       0  4998.1    0.03       0  5007.1    0.05       0
Bank Sta=4998.1,5007.1
Exp/Cntr=0.3,0.1

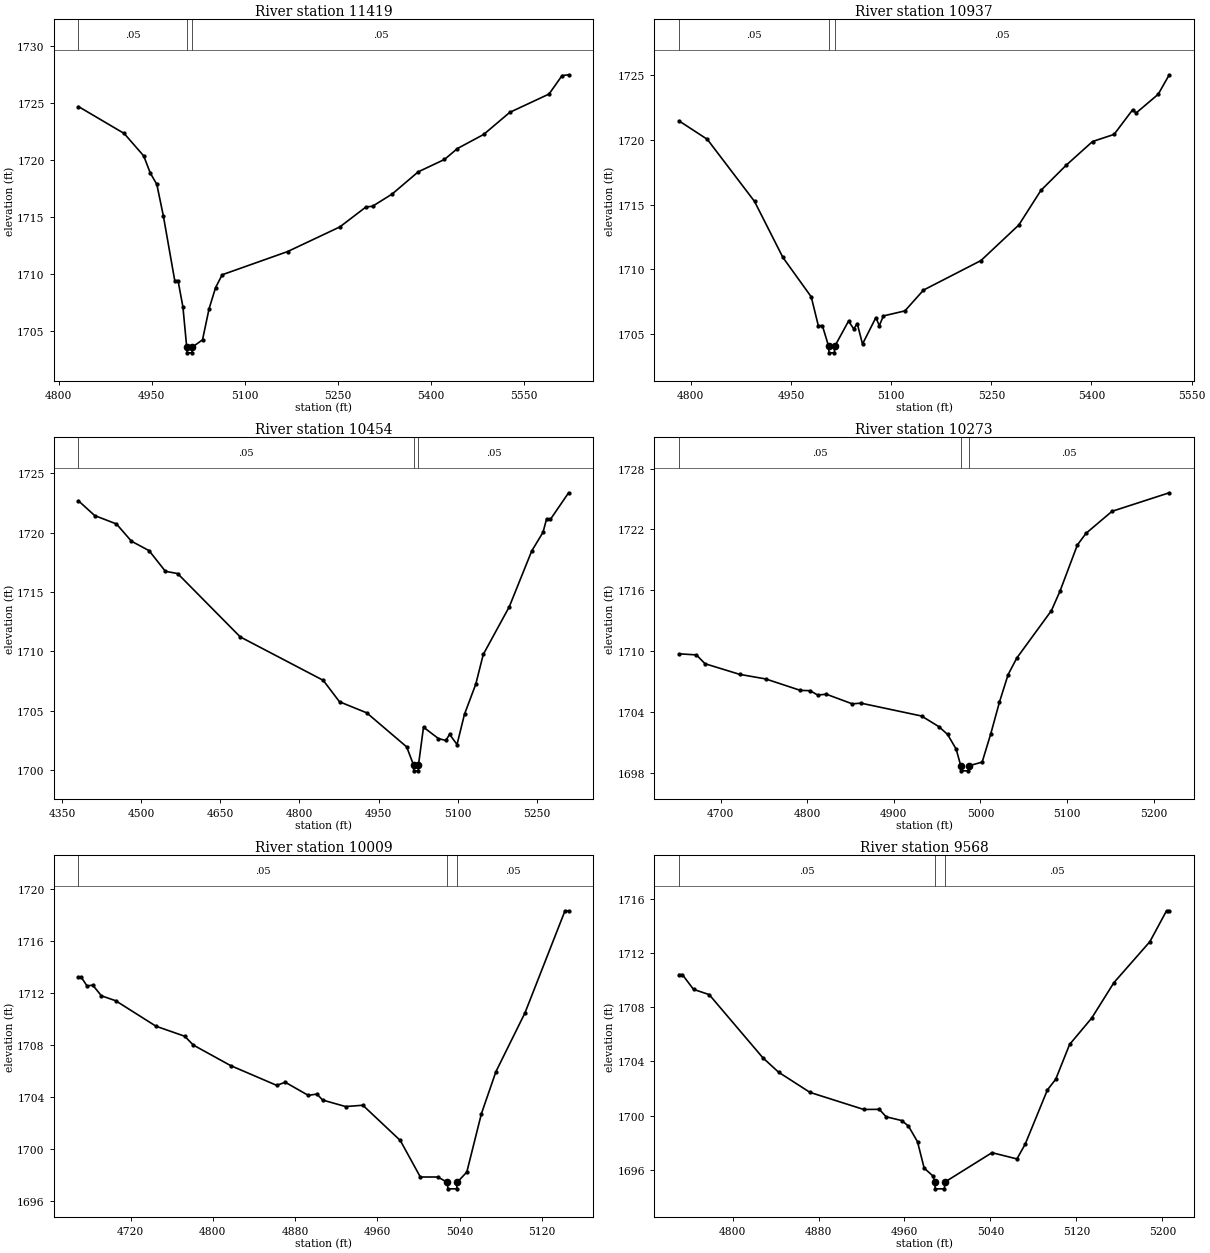
Type RM Length L Ch R = 1,11419,482,482,482
BEGIN DESCRIPTION:
Deadman 40 24.0
END DESCRIPTION:
XS GIS Cut Line= 3
      1635505.03      6908388.01      1635655.00      6908438.00
      1636254.96      6908637.99
#Sta/Elev= 30
  4831.7 1724.67  4905.5 1722.31  4937.1 1720.34  4947.6 1718.85  4958.2 1717.85
  4968.7 1715.10  4987.1 1709.42  4992.4 1709.42  5000.3 1707.11  5006.4 1703.59
  5006.9 1703.09  5014.9 1703.09  5015.4 1703.59  5031.9 1704.23  5042.5 1706.96
  5053.0 1708.81  5063.6 1709.93  5169.0 1711.96  5253.3 1714.12  5295.5 1715.87
  5306.0 1715.93  5337.6 1717.00  5379.8 1718.95  5422.0 1720.03  5443.0 1720.99
  5485.2 1722.22  5527.4 1724.16  5590.6 1725.76  5611.7 1727.38  5622.2 1727.45
#Mann=3,-1,0
  4831.7    0.05       0  5006.4    0.03       0  5015.4    0.05       0
Bank Sta=5006.4,5015.4
Exp/Cntr=0.3,0.1

Type RM Length L Ch R = 1,10937,483,483,483
BEGIN DESCRIPTION:
Deadman 40 23.0
END DESCRIPTION:
XS GIS Cut Line= 3
      1635405.01      6908738.01      1635555.00      6908888.00
      1636054.97      6909037.99
#Sta/Elev= 30
  4782.3 1721.48  4824.7 1720.05  4895.4 1715.24  4937.9 1710.90  4980.3 1707.85
  4990.9 1705.62  4997.0 1705.62  5006.4 1704.01  5006.9 1703.51  5015.0 1703.51
  5015.5 1704.01  5036.2 1705.97  5044.0 1705.36  5049.2 1705.78  5057.1 1704.19
  5077.1 1706.24  5082.3 1705.62  5088.4 1706.37  5120.6 1706.76  5148.4 1708.37
  5234.5 1710.66  5291.1 1713.41  5324.2 1716.09  5362.4 1718.06  5401.6 1719.88
  5433.8 1720.43  5461.6 1722.34  5466.8 1722.09  5499.9 1723.54  5516.4 1725.05
#Mann=3,-1,0
  4782.3    0.05       0  5006.4    0.03       0  5015.5    0.05       0
Bank Sta=5006.4,5015.5
Exp/Cntr=0.3,0.1

Type RM Length L Ch R = 1,10454,181,181,181
BEGIN DESCRIPTION:
Deadman 40 22.0
END DESCRIPTION:
XS GIS Cut Line= 3
      1635305.00      6908737.98      1635455.00      6909338.00
      1635670.27      6909561.50
#Sta/Elev= 30
  4381.2 1722.70  4412.1 1721.45  4453.4 1720.74  4481.7 1719.29  4515.2 1718.49
  4546.1 1716.75  4569.3 1716.56  4687.9 1711.22  4845.1 1707.56  4876.0 1705.75
  4927.5 1704.82  5003.2 1701.95  5016.2 1700.43  5016.7 1699.93  5025.1 1699.93
  5025.6 1700.43  5035.1 1703.61  5063.4 1702.65  5077.5 1702.49  5084.5 1703.01
  5098.6 1702.15  5112.8 1704.71  5134.1 1707.23  5148.3 1709.74  5197.6 1713.76
  5240.1 1718.46  5261.5 1720.04  5268.4 1721.18  5275.6 1721.13  5310.0 1723.37
#Mann=3,-1,0
  4381.2    0.05       0  5016.2    0.05       0  5025.6    0.05       0
Bank Sta=5016.2,5025.6
Exp/Cntr=0.3,0.1

Type RM Length L Ch R = 1,10273,264,264,264
BEGIN DESCRIPTION:
Mapping XS 7cc9069f
END DESCRIPTION:
XS GIS Cut Line= 2
      1635307.30      6909087.87      1635317.66      6909654.08
#Sta/Elev= 30
  4651.8 1709.72  4671.9 1709.61  4681.9 1708.74  4721.9 1707.69  4751.9 1707.24
  4792.0 1706.11  4803.2 1706.08  4812.0 1705.65  4822.0 1705.73  4852.0 1704.78
  4862.0 1704.85  4932.0 1703.58  4952.0 1702.53  4962.0 1701.77  4972.0 1700.31
  4977.3 1698.67  4977.8 1698.17  4986.2 1698.17  4986.7 1698.67  5002.0 1699.03
  5012.0 1701.84  5022.0 1704.96  5032.0 1707.67  5042.0 1709.30  5082.0 1713.98
  5092.0 1715.92  5112.0 1720.46  5122.0 1721.61  5152.0 1723.78  5218.1 1725.61
#Mann=3,-1,0
  4651.8    0.05       0  4977.3    0.05       0  4986.7    0.05       0
Bank Sta=4977.3,4986.7
Exp/Cntr=0.3,0.1

Type RM Length L Ch R = 1,10009,441,441,441
BEGIN DESCRIPTION:
Deadman 40 21.0
END DESCRIPTION:
XS GIS Cut Line= 3
      1635255.00      6908988.00      1635105.00      6909288.00
      1635005.02      6909387.98
#Sta/Elev= 30
  4669.2 1713.20  4672.0 1713.20  4677.6 1712.53  4683.2 1712.59  4691.6 1711.77
  4705.5 1711.39  4744.7 1709.43  4772.6 1708.66  4781.0 1707.98  4817.3 1706.40
  4862.1 1704.88  4870.4 1705.12  4892.8 1704.11  4901.2 1704.21  4906.8 1703.75
  4929.1 1703.25  4945.9 1703.35  4982.3 1700.64  5001.8 1697.83  5018.8 1697.83
  5028.1 1697.42  5028.6 1696.92  5037.1 1696.92  5037.6 1697.42  5047.0 1698.21
  5061.2 1702.70  5075.3 1705.93  5103.6 1710.46  5142.5 1718.31  5146.0 1718.31
#Mann=3,-1,0
  4669.2    0.05       0  5028.1    0.05       0  5037.6    0.05       0
Bank Sta=5028.1,5037.6
Exp/Cntr=0.3,0.1

Type RM Length L Ch R = 1,9568,408,408,408
BEGIN DESCRIPTION:
Deadman 40 20.0
END DESCRIPTION:
XS GIS Cut Line= 3
      1634904.99      6908838.01      1634755.00      6909038.00
      1634705.01      6909237.95
#Sta/Elev= 30
  4750.2 1710.41  4753.3 1710.41  4763.7 1709.32  4778.3 1708.93  4828.3 1704.26
  4842.9 1703.20  4872.1 1701.71  4922.1 1700.45  4936.6 1700.46  4942.9 1699.91
  4957.5 1699.63  4963.7 1699.22  4972.1 1698.07  4978.3 1696.12  4986.6 1695.53
  4988.1 1695.09  4988.6 1694.59  4997.1 1694.59  4997.6 1695.09  5041.4 1697.26
  5064.6 1696.80  5072.3 1697.89  5093.0 1701.90  5100.7 1702.68  5113.6 1705.25
  5134.2 1707.20  5154.8 1709.81  5188.3 1712.84  5203.8 1715.12  5206.3 1715.12
#Mann=3,-1,0
  4750.2    0.05       0  4988.1    0.03       0  4997.6    0.05       0
Bank Sta=4988.1,4997.6
Exp/Cntr=0.3,0.1

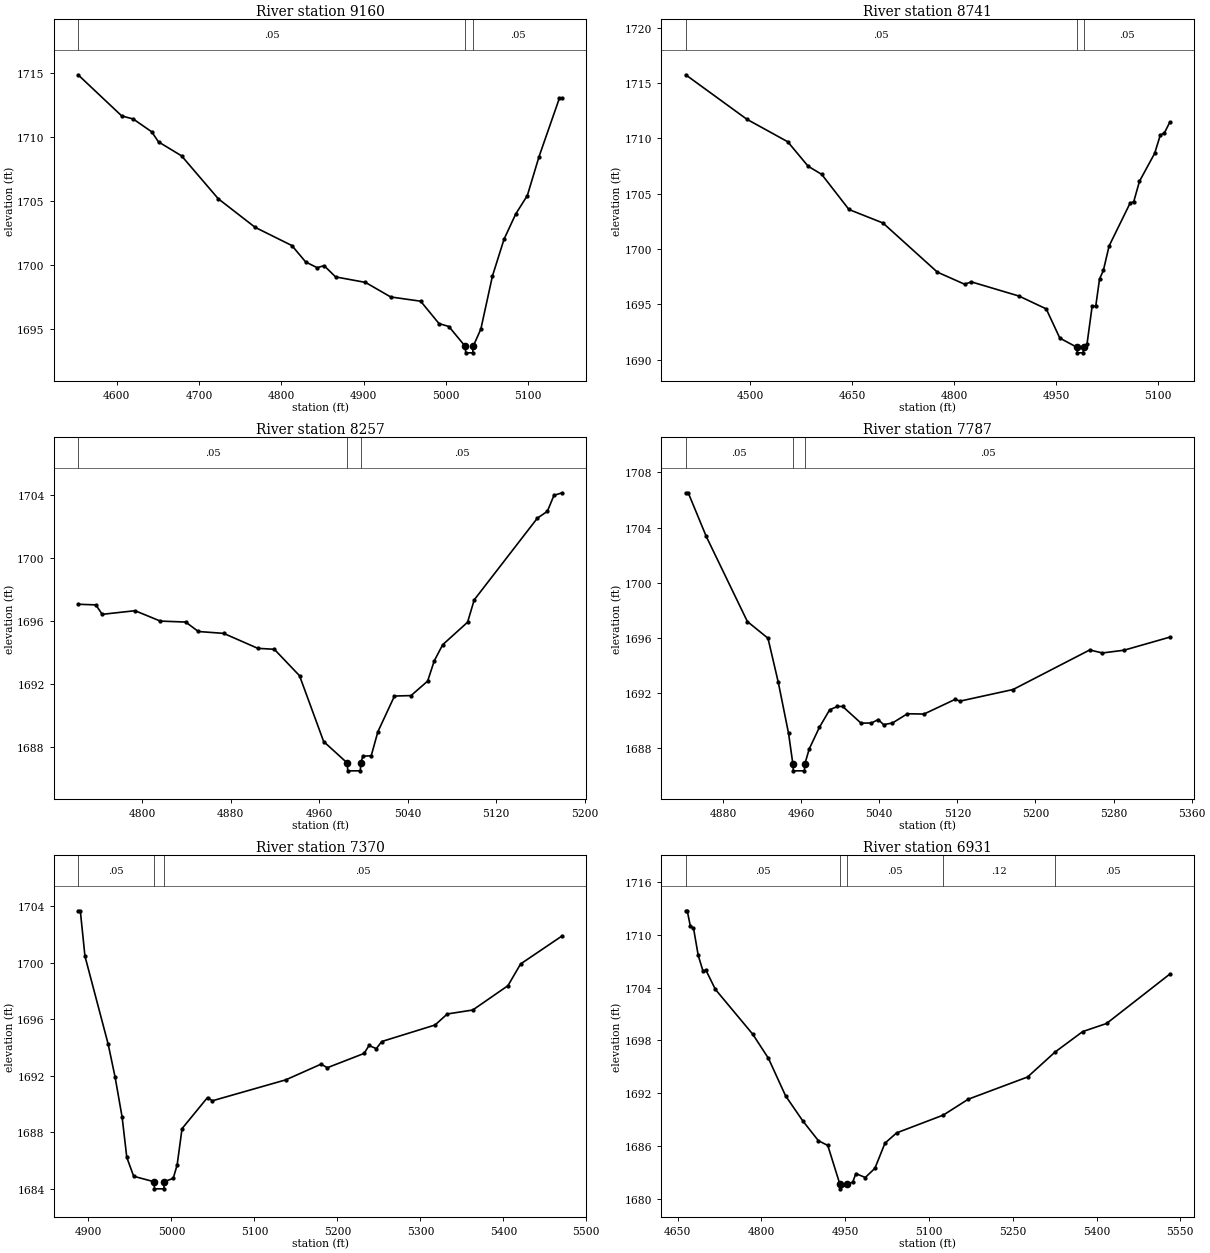
Type RM Length L Ch R = 1,9160,419,419,419
BEGIN DESCRIPTION:
Deadman 40 19.0
END DESCRIPTION:
XS GIS Cut Line= 3
      1634855.02      6908587.99      1634455.00      6908788.00
      1634354.97      6908888.03
#Sta/Elev= 30
  4552.9 1714.86  4606.0 1711.64  4620.0 1711.40  4642.4 1710.40  4650.7 1709.61
  4678.7 1708.52  4723.4 1705.16  4768.1 1702.93  4812.9 1701.50  4829.6 1700.22
  4843.6 1699.77  4852.0 1699.93  4866.0 1699.05  4902.3 1698.62  4933.0 1697.48
  4969.4 1697.15  4991.7 1695.40  5003.7 1695.17  5023.7 1693.61  5024.2 1693.11
  5032.7 1693.11  5033.2 1693.61  5042.6 1694.97  5056.7 1699.12  5070.8 1702.00
  5085.0 1703.97  5099.1 1705.41  5113.3 1708.45  5138.0 1713.01  5141.6 1713.01
#Mann=3,-1,0
  4552.9    0.05       0  5023.7    0.03       0  5033.2    0.05       0
Bank Sta=5023.7,5033.2
Exp/Cntr=0.3,0.1

Type RM Length L Ch R = 1,8741,484,484,484
BEGIN DESCRIPTION:
Deadman 40 18.0
END DESCRIPTION:
XS GIS Cut Line= 3
      1634855.00      6908438.00      1634255.00      6908438.00
      1634155.00      6908488.00
#Sta/Elev= 30
  4405.5 1715.75  4495.5 1711.73  4555.5 1709.70  4585.5 1707.49  4605.5 1706.75
  4645.5 1703.58  4695.5 1702.36  4775.5 1697.92  4815.5 1696.83  4825.5 1697.04
  4895.5 1695.76  4935.5 1694.60  4955.5 1691.96  4980.7 1691.13  4981.2 1690.63
  4989.8 1690.63  4990.3 1691.13  4995.5 1691.44  5003.0 1694.84  5008.3 1694.84
  5013.9 1697.31  5019.5 1698.07  5027.9 1700.28  5058.6 1704.13  5064.2 1704.30
  5072.6 1706.13  5094.9 1708.65  5103.3 1710.32  5108.9 1710.46  5117.3 1711.48
#Mann=3,-1,0
  4405.5    0.05       0  4980.7    0.05       0  4990.3    0.05       0
Bank Sta=4980.7,4990.3
Exp/Cntr=0.3,0.1

Type RM Length L Ch R = 1,8257,470,470,470
BEGIN DESCRIPTION:
Deadman 40 17.0
END DESCRIPTION:
XS GIS Cut Line= 3
      1634380.04      6907862.98      1634155.00      6907988.00
      1634055.01      6908137.99
#Sta/Elev= 30
  4742.2 1697.08  4758.3 1697.04  4764.0 1696.44  4793.7 1696.67  4816.6 1696.01
  4839.5 1695.95  4850.9 1695.35  4873.8 1695.23  4904.7 1694.28  4919.6 1694.22
  4942.4 1692.54  4964.2 1688.36  4985.5 1687.00  4986.0 1686.50  4997.3 1686.50
  4997.8 1687.00  4999.6 1687.43  5007.2 1687.46  5013.2 1688.98  5028.2 1691.25
  5043.2 1691.28  5058.2 1692.20  5064.2 1693.49  5071.8 1694.51  5094.3 1695.94
  5100.3 1697.36  5157.4 1702.55  5166.4 1702.98  5172.4 1704.00  5179.9 1704.16
#Mann=3,-1,0
  4742.2    0.05       0  4985.5    0.03       0  4997.8    0.05       0
Bank Sta=4985.5,4997.8
Exp/Cntr=0.3,0.1

Type RM Length L Ch R = 1,7787,417,417,417
BEGIN DESCRIPTION:
Deadman 40 16.0
END DESCRIPTION:
XS GIS Cut Line= 3
      1634004.99      6907438.02      1633955.00      6907588.00
      1633831.02      6907902.34
#Sta/Elev= 30
  4841.7 1706.52  4844.3 1706.52  4862.8 1703.35  4904.9 1697.18  4926.0 1695.97
  4936.5 1692.79  4947.1 1689.06  4951.5 1686.85  4952.0 1686.35  4963.3 1686.35
  4963.8 1686.85  4968.2 1687.93  4978.7 1689.51  4989.2 1690.78  4997.2 1691.02
  5002.5 1691.02  5021.3 1689.81  5032.0 1689.82  5039.0 1690.07  5044.4 1689.70
  5053.5 1689.82  5068.8 1690.49  5085.8 1690.47  5117.6 1691.53  5122.9 1691.41
  5177.1 1692.25  5255.6 1695.12  5268.5 1694.90  5290.7 1695.10  5337.7 1696.05
#Mann=3,-1,0
  4841.7    0.05       0  4951.5    0.05       0  4963.8    0.05       0
Bank Sta=4951.5,4963.8
Exp/Cntr=0.3,0.1

Type RM Length L Ch R = 1,7370,439,439,439
BEGIN DESCRIPTION:
Deadman 40 15.0
END DESCRIPTION:
XS GIS Cut Line= 3
      1633555.02      6907538.04      1633605.00      6907638.00
      1633855.02      6908038.04
#Sta/Elev= 30
  4887.5 1703.67  4890.2 1703.67  4895.8 1700.46  4923.8 1694.23  4932.2 1691.88
  4940.6 1689.07  4946.2 1686.23  4954.5 1684.89  4979.1 1684.50  4979.6 1684.00
  4990.9 1684.00  4991.4 1684.50  5002.2 1684.75  5006.9 1685.69  5012.8 1688.26
  5043.5 1690.46  5049.4 1690.23  5137.8 1691.71  5180.3 1692.82  5187.9 1692.57
  5232.2 1693.58  5238.1 1694.14  5246.9 1693.92  5253.4 1694.42  5317.7 1695.59
  5332.4 1696.37  5363.1 1696.65  5405.5 1698.37  5420.8 1699.91  5471.0 1701.90
#Mann=3,-1,0
  4887.5    0.05       0  4979.1    0.03       0  4991.4    0.05       0
Bank Sta=4979.1,4991.4
Exp/Cntr=0.3,0.1

Type RM Length L Ch R = 1,6931,439,439,439
BEGIN DESCRIPTION:
Deadman 40 14.0
END DESCRIPTION:
XS GIS Cut Line= 3
      1633004.98      6907787.99      1633305.00      6907938.00
      1633704.97      6908287.97
#Sta/Elev= 30
  4664.4 1712.76  4667.2 1712.76  4672.8 1710.99  4678.4 1710.80  4686.8 1707.70
  4695.2 1705.94  4700.8 1705.98  4717.5 1703.82  4784.6 1698.70  4812.6 1695.96
  4843.3 1691.69  4874.1 1688.84  4902.0 1686.59  4918.8 1686.05  4940.6 1681.61
  4941.1 1681.11  4952.9 1681.61  4963.5 1681.88  4969.1 1682.85  4985.9 1682.40
  5003.2 1683.45  5021.2 1686.31  5042.1 1687.48  5125.8 1689.51  5170.2 1691.31
  5276.5 1693.84  5325.5 1696.67  5375.2 1699.01  5417.9 1699.93  5531.3 1705.56
#Mann=5,-1,0
  4664.4    0.05       0  4940.6    0.05       0  4952.9    0.05       0
  5125.8    0.12       0  5325.5    0.05       0
Bank Sta=4940.6,4952.9
Exp/Cntr=0.3,0.1

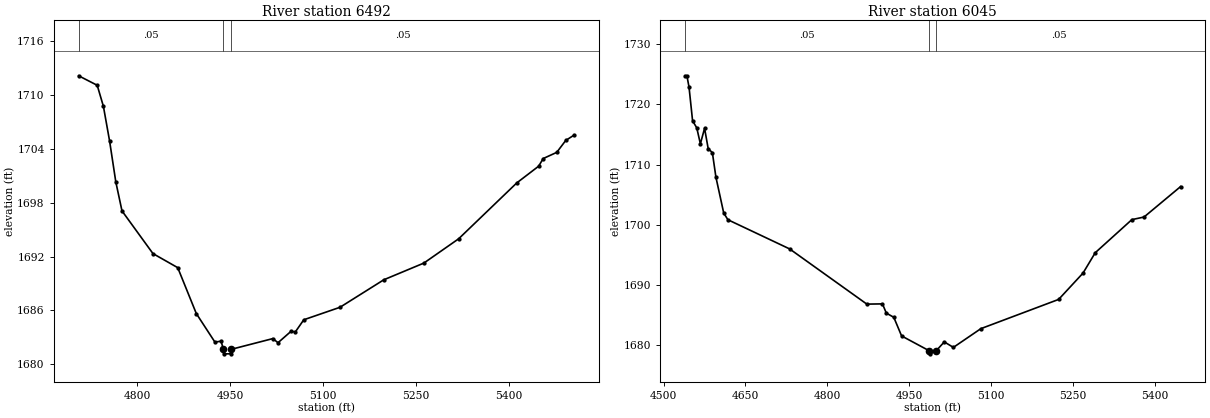
Type RM Length L Ch R = 1,6492,447,447,447
BEGIN DESCRIPTION:
Deadman 40 13.0
END DESCRIPTION:
XS GIS Cut Line= 3
      1633005.00      6907938.02      1633005.00      6908238.00
      1633305.01      6908638.02
#Sta/Elev= 30
  4705.8 1712.16  4735.8 1711.10  4745.8 1708.75  4755.8 1704.88  4765.8 1700.33
  4775.8 1697.09  4825.8 1692.33  4865.8 1690.76  4895.8 1685.64  4925.8 1682.46
  4935.8 1682.56  4939.5 1681.65  4940.0 1681.15  4951.5 1681.15  4952.0 1681.65
  5019.3 1682.85  5027.7 1682.39  5048.5 1683.65  5055.8 1683.61  5069.3 1684.95
  5127.7 1686.34  5198.5 1689.41  5263.1 1691.27  5319.3 1693.98  5413.1 1700.21
  5448.5 1702.08  5455.8 1702.93  5477.7 1703.62  5492.2 1704.95  5505.8 1705.55
#Mann=3,-1,0
  4705.8    0.05       0  4939.5    0.03       0  4952.0    0.05       0
Bank Sta=4939.5,4952
Exp/Cntr=0.3,0.1

Type RM Length L Ch R = 1,6045,443,443,443
BEGIN DESCRIPTION:
Deadman 40 12.0
END DESCRIPTION:
XS GIS Cut Line= 3
      1632304.98      6908187.98      1632655.00      6908488.00
      1632854.99      6908887.99
#Sta/Elev= 30
  4539.3 1724.73  4542.6 1724.73  4546.5 1722.86  4553.0 1717.27  4560.7 1716.08
  4567.3 1713.44  4575.0 1716.01  4581.6 1712.65  4589.3 1711.97  4595.8 1707.90
  4610.1 1701.95  4617.8 1700.84  4730.9 1696.00  4872.4 1686.84  4901.0 1686.88
  4908.1 1685.35  4921.8 1684.65  4936.1 1681.56  4986.9 1679.09  4987.4 1678.59
  4999.4 1679.09  5014.3 1680.57  5031.0 1679.66  5081.4 1682.77  5223.9 1687.62
  5268.6 1691.99  5291.0 1695.37  5358.1 1700.86  5380.4 1701.29  5447.5 1706.35
#Mann=3,-1,0
  4539.3    0.05       0  4986.9    0.03       0  4999.4    0.05       0
Bank Sta=4986.9,4999.4
Exp/Cntr=0.3,0.1