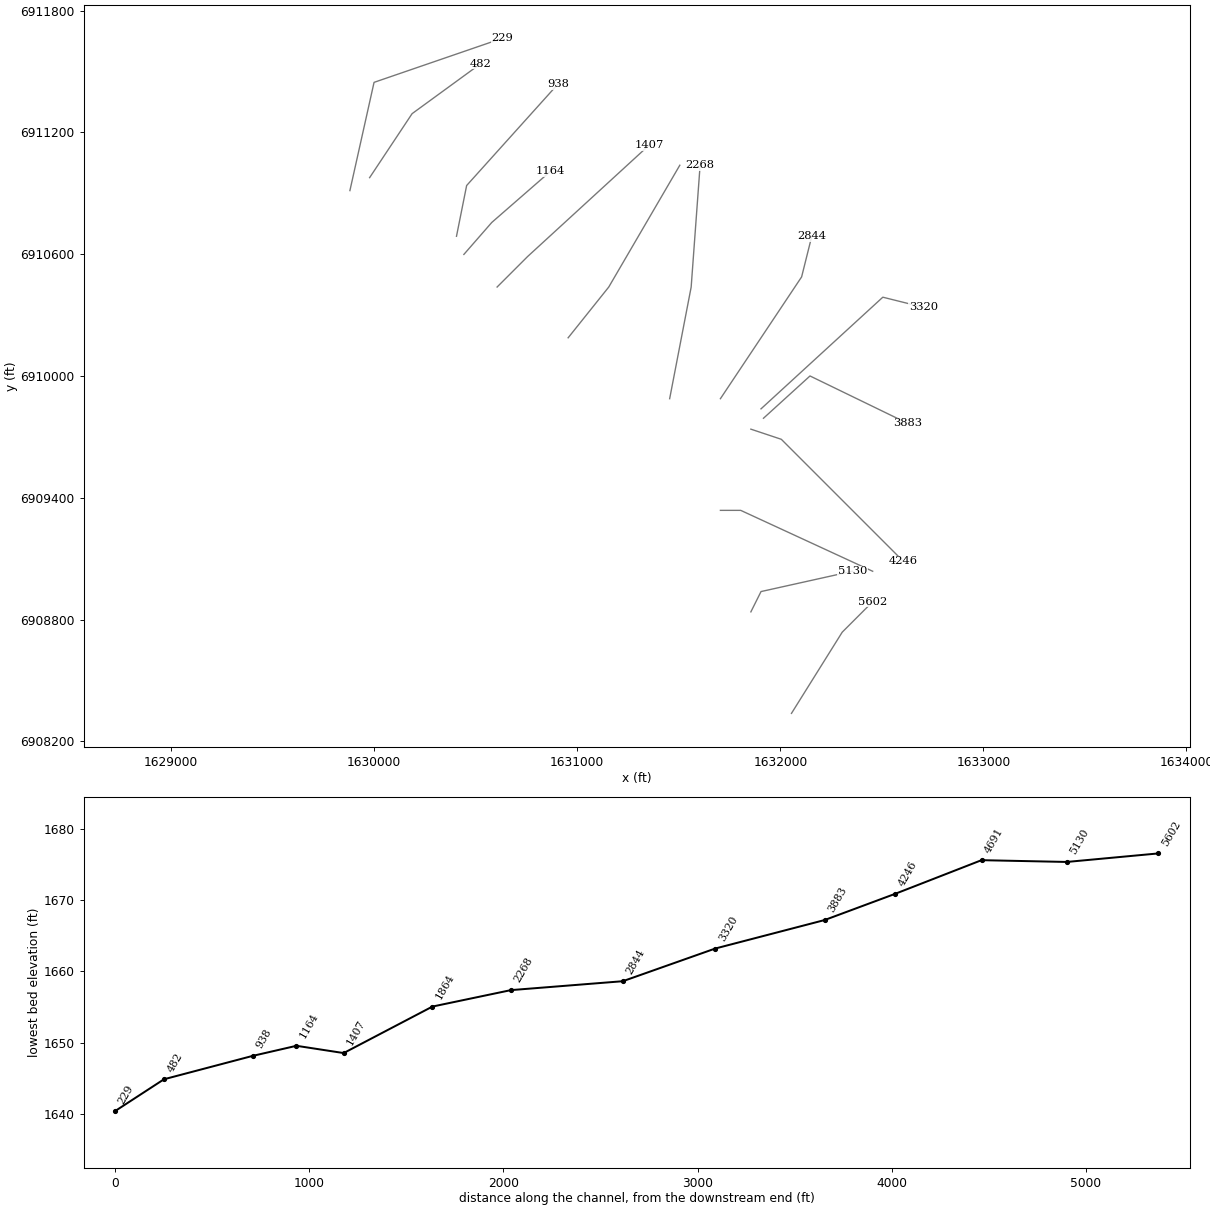
HEC-RAS study Deadman 40.prj: Deadman 40 Base Level Engineering

--- Deadman 40.g01 (geometry) --- (continued)

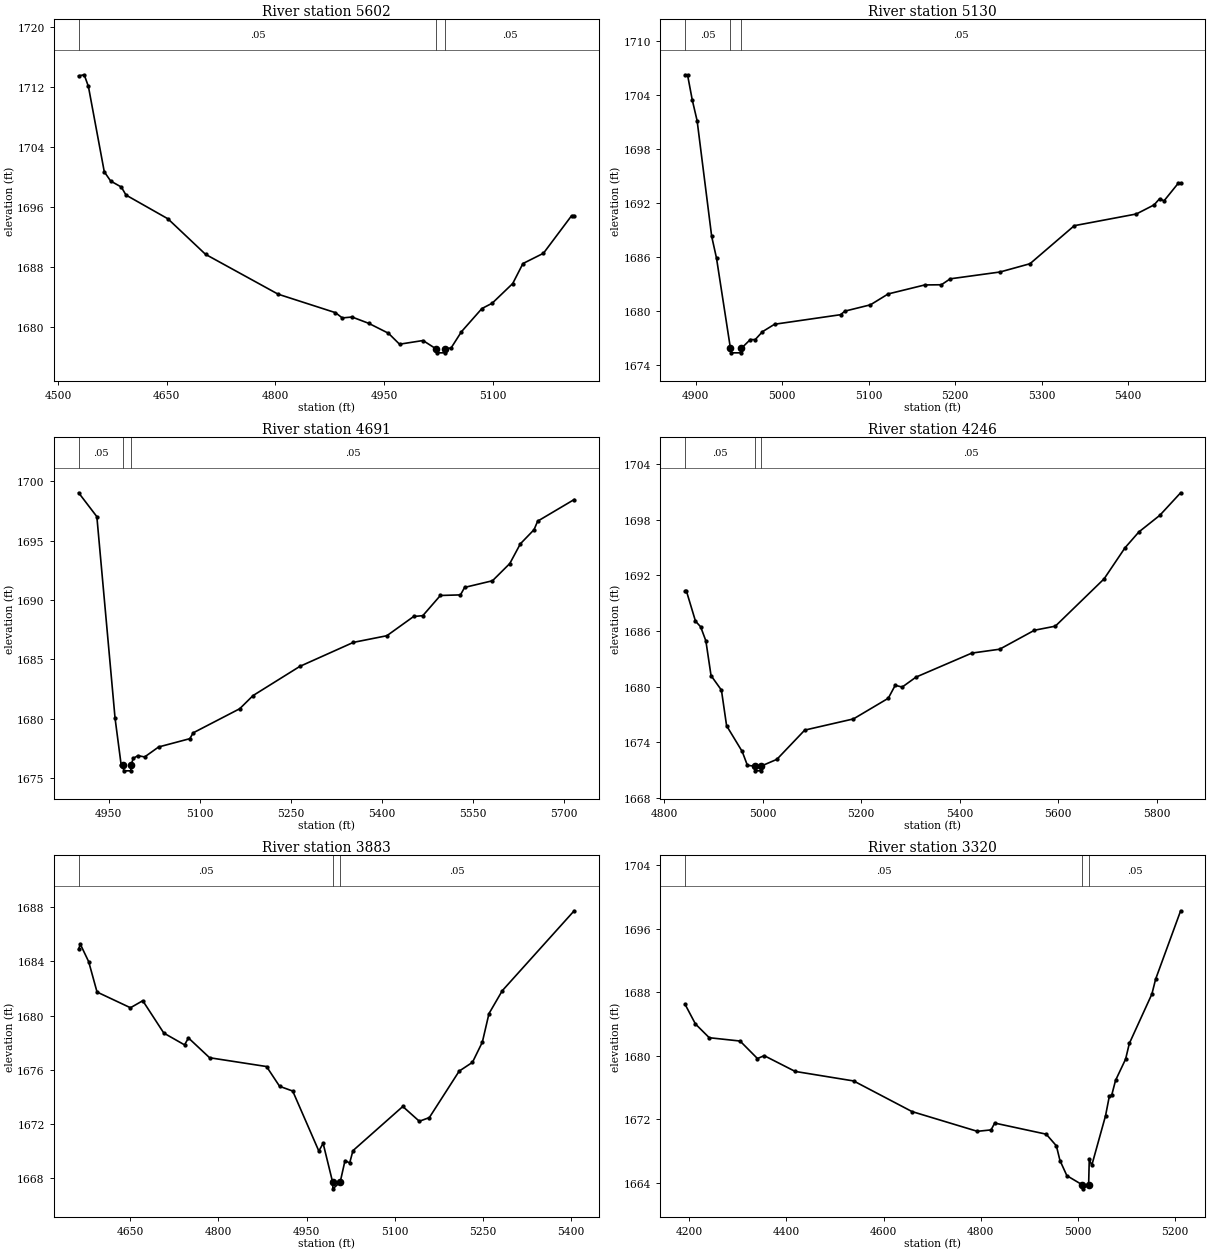
Type RM Length L Ch R = 1,5602,472,472,472
BEGIN DESCRIPTION:
Deadman 40 11.0
END DESCRIPTION:
XS GIS Cut Line= 3
      1632055.01      6908338.01      1632305.00      6908738.00
      1632454.99      6908887.99
#Sta/Elev= 30
  4528.6 1713.46  4536.3 1713.60  4542.1 1712.04  4564.0 1700.68  4572.8 1699.45
  4587.5 1698.65  4594.0 1697.58  4651.8 1694.42  4703.7 1689.69  4803.9 1684.38
  4883.0 1681.92  4892.4 1681.22  4905.9 1681.34  4928.9 1680.50  4956.1 1679.18
  4971.4 1677.72  5003.8 1678.21  5022.3 1677.07  5022.8 1676.57  5034.3 1676.57
  5034.8 1677.07  5042.7 1677.24  5056.9 1679.39  5085.1 1682.47  5099.3 1683.18
  5127.6 1685.80  5141.7 1688.46  5170.0 1689.83  5208.9 1694.84  5212.4 1694.84
#Mann=3,-1,0
  4528.6    0.05       0  5022.3    0.03       0  5034.8    0.05       0
Bank Sta=5022.3,5034.8
Exp/Cntr=0.3,0.1

Type RM Length L Ch R = 1,5130,439,439,439
BEGIN DESCRIPTION:
Deadman 40 10.0
END DESCRIPTION:
XS GIS Cut Line= 3
      1631855.02      6908838.03      1631905.00      6908938.00
      1632354.96      6909037.99
#Sta/Elev= 30
  4887.9 1706.29  4890.7 1706.29  4896.2 1703.48  4901.8 1701.18  4918.6 1688.33
  4924.2 1685.90  4940.3 1675.87  4940.8 1675.37  4952.4 1675.37  4952.9 1675.87
  4963.3 1676.85  4968.9 1676.84  4977.3 1677.72  4991.3 1678.55  5067.5 1679.61
  5072.7 1680.01  5102.1 1680.71  5122.6 1681.92  5164.9 1682.92  5184.1 1682.94
  5194.3 1683.60  5251.9 1684.36  5286.5 1685.28  5337.7 1689.51  5409.4 1690.81
  5429.9 1691.82  5436.3 1692.51  5441.4 1692.27  5458.1 1694.26  5460.6 1694.26
#Mann=3,-1,0
  4887.9    0.05       0  4940.3    0.03       0  4952.9    0.05       0
Bank Sta=4940.3,4952.9
Exp/Cntr=0.3,0.1

Type RM Length L Ch R = 1,4691,445,445,445
BEGIN DESCRIPTION:
Deadman 40 9.0
END DESCRIPTION:
XS GIS Cut Line= 3
      1631705.00      6909338.00      1631805.00      6909338.00
      1632455.01      6909037.99
#Sta/Elev= 30
  4900.5 1699.04  4930.5 1697.03  4960.5 1680.04  4970.5 1676.13  4974.2 1676.12
  4974.7 1675.62  4986.3 1675.62  4986.8 1676.12  4990.5 1676.67  4998.0 1676.90
  5009.2 1676.79  5032.2 1677.63  5083.6 1678.33  5089.1 1678.82  5165.7 1680.85
  5187.7 1681.96  5264.8 1684.42  5352.9 1686.44  5408.0 1687.00  5452.1 1688.62
  5467.2 1688.69  5496.1 1690.39  5529.2 1690.44  5536.0 1691.07  5581.9 1691.63
  5610.4 1693.08  5627.8 1694.74  5650.3 1695.93  5656.3 1696.65  5716.4 1698.47
#Mann=3,-1,0
  4900.5    0.05       0  4974.2    0.05       0  4986.8    0.05       0
Bank Sta=4974.2,4986.8
Exp/Cntr=0.3,0.1

Type RM Length L Ch R = 1,4246,363,363,363
BEGIN DESCRIPTION:
Deadman 40 8.0
END DESCRIPTION:
XS GIS Cut Line= 3
      1631854.99      6909738.00      1632005.00      6909688.00
      1632604.96      6909088.04
#Sta/Elev= 30
  4842.4 1690.33  4845.0 1690.33  4863.5 1687.06  4874.0 1686.45  4884.6 1684.93
  4895.1 1681.18  4916.2 1679.61  4926.7 1675.76  4958.4 1672.98  4968.9 1671.49
  4983.7 1671.39  4984.2 1670.89  4995.8 1670.89  4996.3 1671.39  5028.8 1672.13
  5085.4 1675.29  5184.4 1676.50  5255.1 1678.73  5269.2 1680.13  5283.4 1679.94
  5311.6 1681.02  5424.8 1683.61  5481.4 1684.03  5552.1 1686.08  5594.5 1686.52
  5693.5 1691.63  5735.9 1694.98  5764.2 1696.70  5806.6 1698.49  5849.0 1700.93
#Mann=3,-1,0
  4842.4    0.05       0  4983.7    0.05       0  4996.3    0.05       0
Bank Sta=4983.7,4996.3
Exp/Cntr=0.3,0.1

Type RM Length L Ch R = 1,3883,563,563,563
BEGIN DESCRIPTION:
Mapping XS a1584e22
END DESCRIPTION:
XS GIS Cut Line= 3
      1631917.10      6909791.68      1632146.25      6910000.00
      1632625.38      6909767.38
#Sta/Elev= 30
  4562.6 1684.91  4565.5 1685.27  4579.7 1683.98  4593.9 1681.74  4650.7 1680.58
  4671.6 1681.10  4707.4 1678.71  4742.6 1677.84  4749.3 1678.35  4785.2 1676.89
  4882.0 1676.24  4904.2 1674.78  4926.5 1674.43  4970.9 1670.00  4978.2 1670.57
  4994.3 1667.71  4994.8 1667.21  5007.2 1667.71  5015.4 1669.30  5023.3 1669.12
  5028.9 1670.03  5113.6 1673.29  5141.7 1672.20  5158.7 1672.47  5209.4 1675.90
  5232.0 1676.55  5248.8 1678.04  5260.1 1680.15  5282.7 1681.84  5404.9 1687.74
#Mann=3,-1,0
  4562.6    0.05       0  4994.3    0.05       0  5007.2    0.05       0
Bank Sta=4994.3,5007.2
Exp/Cntr=0.3,0.1

Type RM Length L Ch R = 1,3320,476,476,476
BEGIN DESCRIPTION:
Deadman 40 7.0
END DESCRIPTION:
XS GIS Cut Line= 3
      1631904.97      6909837.97      1632505.00      6910388.00
      1632704.97      6910338.01
#Sta/Elev= 30
  4191.4 1686.46  4212.7 1683.99  4241.1 1682.26  4304.6 1681.84  4340.4 1679.63
  4354.2 1680.00  4418.0 1678.01  4538.3 1676.81  4658.5 1672.95  4793.0 1670.46
  4821.3 1670.64  4828.7 1671.50  4934.8 1670.10  4955.7 1668.63  4963.1 1666.78
  4977.3 1664.87  5009.2 1663.71  5009.7 1663.21  5022.1 1663.71  5023.4 1666.91
  5028.6 1666.18  5056.9 1672.42  5064.7 1674.88  5069.8 1675.06  5077.5 1676.88
  5098.2 1679.56  5105.9 1681.54  5152.3 1687.76  5160.0 1689.64  5211.5 1698.26
#Mann=3,-1,0
  4191.4    0.05       0  5009.2    0.05       0  5022.1    0.05       0
Bank Sta=5009.2,5022.1
Exp/Cntr=0.3,0.1

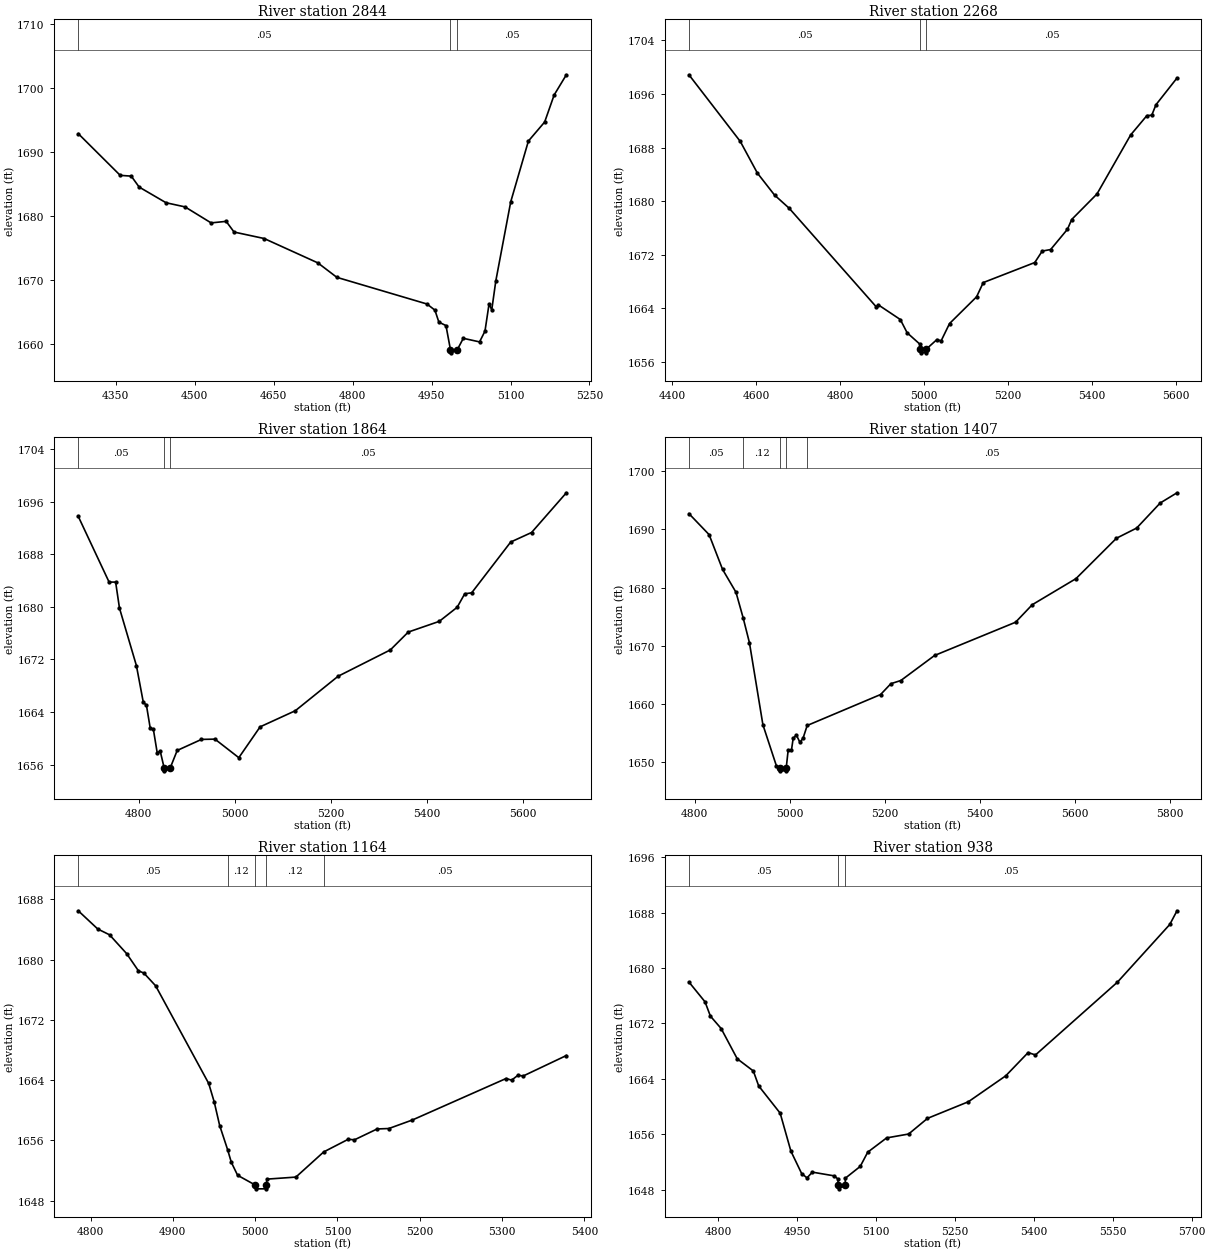
Type RM Length L Ch R = 1,2844,576,576,576
BEGIN DESCRIPTION:
Deadman 40 6.0
END DESCRIPTION:
XS GIS Cut Line= 3
      1631704.98      6909887.97      1632105.00      6910488.00
      1632155.00      6910688.00
#Sta/Elev= 30
  4278.8 1692.88  4358.5 1686.36  4379.5 1686.24  4394.5 1684.53  4445.6 1682.08
  4481.7 1681.43  4531.2 1678.93  4559.8 1679.17  4574.8 1677.50  4631.9 1676.49
  4734.0 1672.68  4770.1 1670.42  4941.4 1666.25  4956.4 1665.29  4963.9 1663.42
  4977.4 1662.88  4985.9 1659.12  4986.4 1658.62  4999.0 1659.12  5010.3 1660.89
  5041.2 1660.33  5051.5 1662.01  5059.2 1666.24  5064.4 1665.35  5072.1 1669.87
  5100.4 1682.22  5134.0 1691.72  5164.9 1694.70  5182.9 1698.92  5206.1 1702.08
#Mann=3,-1,0
  4278.8    0.05       0  4985.9    0.05       0  4999.0    0.05       0
Bank Sta=4985.9,4999
Exp/Cntr=0.3,0.1

Type RM Length L Ch R = 1,2268,404,404,404
BEGIN DESCRIPTION:
Deadman 40 5.0
END DESCRIPTION:
XS GIS Cut Line= 3
      1631455.00      6909888.01      1631560.91      6910437.70
      1631605.00      6911037.98
#Sta/Elev= 30
  4440.2 1698.85  4562.4 1688.91  4603.1 1684.19  4643.9 1680.91  4678.8 1678.94
  4886.3 1664.21  4891.4 1664.51  4943.3 1662.34  4959.6 1660.36  4990.1 1658.65
  4991.1 1657.87  4991.6 1657.37  5003.7 1657.37  5004.2 1657.87  5030.4 1659.35
  5040.4 1659.15  5060.5 1661.74  5124.9 1665.73  5140.7 1667.85  5263.3 1670.84
  5281.1 1672.55  5301.1 1672.78  5341.2 1675.81  5351.2 1677.26  5411.4 1681.07
  5491.6 1689.88  5530.2 1692.76  5541.8 1692.82  5551.8 1694.38  5601.9 1698.37
#Mann=3,-1,0
  4440.2    0.05       0  4991.1    0.05       0  5004.2    0.05       0
Bank Sta=4991.1,5004.2
Exp/Cntr=0.3,0.1

Type RM Length L Ch R = 1,1864,457,457,457
BEGIN DESCRIPTION:
Deadman 40 4.0
END DESCRIPTION:
XS GIS Cut Line= 3
      1630954.97      6910187.96      1631155.00      6910438.00
      1631504.99      6911037.98
#Sta/Elev= 30
  4674.6 1693.75  4738.7 1683.76  4752.3 1683.76  4760.3 1679.80  4795.5 1671.06
  4809.9 1665.46  4816.3 1665.06  4824.3 1661.52  4830.7 1661.40  4838.7 1657.82
  4845.1 1658.03  4853.0 1655.56  4853.5 1655.06  4866.1 1655.56  4880.3 1658.16
  4930.8 1659.84  4958.8 1659.88  5008.4 1657.06  5052.7 1661.75  5125.9 1664.20
  5214.8 1669.44  5323.5 1673.45  5360.7 1676.16  5425.2 1677.79  5462.4 1679.93
  5478.1 1681.98  5492.6 1682.13  5573.7 1689.85  5617.1 1691.30  5689.4 1697.34
#Mann=3,-1,0
  4674.6    0.05       0  4853.0    0.05       0  4866.1    0.05       0
Bank Sta=4853,4866.1
Exp/Cntr=0.3,0.1

Type RM Length L Ch R = 1,1407,243,243,243
BEGIN DESCRIPTION:
Deadman 40 3.0
END DESCRIPTION:
XS GIS Cut Line= 3
      1630605.03      6910438.03      1630755.00      6910588.00
      1631354.98      6911137.98
#Sta/Elev= 30
  4788.2 1692.72  4830.6 1689.11  4858.9 1683.14  4887.1 1679.21  4902.1 1674.84
  4915.4 1670.54  4943.7 1656.45  4972.0 1649.41  4979.5 1649.03  4980.0 1648.53
  4992.2 1648.53  4992.7 1649.03  4996.8 1652.06  5003.7 1652.06  5007.4 1654.14
  5014.2 1654.66  5021.6 1653.41  5028.3 1654.18  5036.8 1656.32  5191.1 1661.64
  5212.7 1663.50  5233.7 1664.05  5304.6 1668.35  5474.8 1674.06  5509.9 1677.07
  5601.8 1681.55  5686.9 1688.49  5729.4 1690.24  5778.8 1694.54  5814.2 1696.30
#Mann=5,-1,0
  4788.2    0.05       0  4902.1    0.12       0  4979.5    0.07       0
  4992.7    0.12       0  5036.8    0.05       0
Bank Sta=4979.5,4992.7
Exp/Cntr=0.3,0.1

Type RM Length L Ch R = 1,1164,226,226,226
BEGIN DESCRIPTION:
Mapping XS b7c97215
END DESCRIPTION:
XS GIS Cut Line= 3
      1630441.37      6910598.61      1630578.89      6910756.18
      1630868.31      6911008.34
#Sta/Elev= 30
  4785.1 1686.47  4808.8 1684.05  4823.1 1683.28  4843.9 1680.78  4858.2 1678.50
  4864.8 1678.20  4879.1 1676.51  4943.6 1663.54  4950.3 1661.08  4956.9 1657.96
  4966.5 1654.77  4971.1 1653.06  4978.7 1651.35  5000.2 1650.05  5000.7 1649.55
  5012.9 1649.55  5013.4 1650.05  5014.4 1650.84  5049.5 1651.11  5083.3 1654.45
  5113.1 1656.13  5120.7 1656.06  5148.2 1657.50  5162.5 1657.56  5191.0 1658.69
  5304.9 1664.20  5311.6 1663.98  5319.2 1664.62  5325.8 1664.54  5378.1 1667.25
#Mann=5,-1,0
  4785.1    0.05       0  4966.5    0.12       0  5000.2    0.07       0
  5013.4    0.12       0  5083.3    0.05       0
Bank Sta=5000.2,5013.4
Exp/Cntr=0.3,0.1

Type RM Length L Ch R = 1,938,456,456,456
BEGIN DESCRIPTION:
Deadman 40 2.0
END DESCRIPTION:
XS GIS Cut Line= 3
      1630405.00      6910687.99      1630455.00      6910938.00
      1630904.97      6911437.96
#Sta/Elev= 30
  4744.6 1677.98  4775.2 1675.12  4785.4 1673.06  4805.8 1671.27  4836.4 1666.90
  4867.0 1665.14  4877.2 1662.98  4918.0 1659.05  4938.4 1653.57  4958.8 1650.34
  4969.0 1649.71  4979.2 1650.54  5020.9 1650.00  5027.6 1649.55  5028.5 1648.63
  5029.0 1648.13  5041.7 1648.63  5041.8 1649.66  5070.2 1651.37  5084.4 1653.42
  5120.3 1655.48  5162.1 1656.04  5198.0 1658.30  5275.7 1660.70  5346.7 1664.44
  5389.3 1667.80  5403.2 1667.45  5559.0 1677.96  5658.4 1686.28  5672.2 1688.26
#Mann=3,-1,0
  4744.6    0.05       0  5028.5    0.03       0  5041.7    0.05       0
Bank Sta=5028.5,5041.7
Exp/Cntr=0.3,0.1

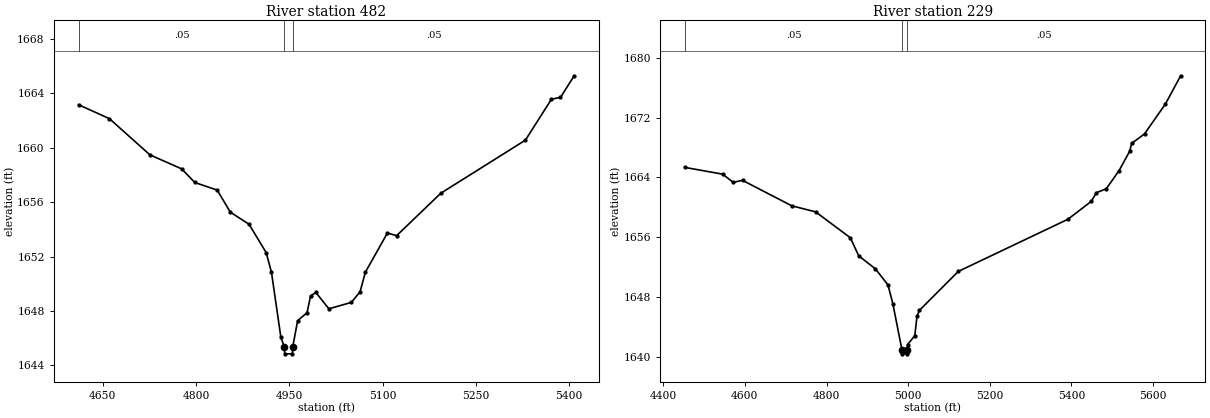
Type RM Length L Ch R = 1,482,253,253,253
BEGIN DESCRIPTION:
Mapping XS cb88a5be
END DESCRIPTION:
XS GIS Cut Line= 3
      1629977.15      6910976.79      1630186.33      6911291.99
      1630524.46      6911538.42
#Sta/Elev= 30
  4611.3 1663.15  4660.8 1662.13  4725.9 1659.47  4777.0 1658.44  4798.0 1657.44
  4834.1 1656.88  4855.2 1655.26  4885.3 1654.37  4912.8 1652.29  4921.3 1650.85
  4936.4 1646.08  4942.1 1645.35  4942.6 1644.85  4955.0 1644.85  4955.5 1645.35
  4963.4 1647.29  4978.5 1647.87  4984.2 1649.10  4992.7 1649.36  5013.6 1648.16
  5049.8 1648.63  5063.8 1649.41  5072.3 1650.85  5107.8 1653.73  5122.5 1653.53
  5193.6 1656.65  5329.6 1660.55  5371.5 1663.56  5386.0 1663.69  5408.0 1665.28
#Mann=3,-1,0
  4611.3    0.05       0  4942.1    0.03       0  4955.5    0.05       0
Bank Sta=4942.1,4955.5
Exp/Cntr=0.3,0.1

Type RM Length L Ch R = 1,229,0,0,0
BEGIN DESCRIPTION:
Deadman 40 1.0
END DESCRIPTION:
XS GIS Cut Line= 3
      1629880.00      6910912.99      1629998.96      6911446.18
      1630630.05      6911663.02
#Sta/Elev= 30
  4453.7 1665.33  4545.7 1664.43  4571.5 1663.33  4594.3 1663.60  4715.0 1660.19
  4773.3 1659.38  4858.4 1655.91  4878.9 1653.49  4919.9 1651.74  4950.6 1649.59
  4962.4 1647.10  4984.9 1640.86  4985.4 1640.36  4997.8 1640.36  4998.3 1640.86
  4998.4 1641.59  5016.3 1642.80  5021.6 1645.40  5027.5 1646.18  5122.7 1651.40
  5391.3 1658.39  5448.5 1660.79  5461.1 1661.95  5485.1 1662.47  5516.3 1664.89
  5542.3 1667.48  5547.5 1668.56  5578.8 1669.82  5630.2 1673.85  5667.3 1677.61
#Mann=3,-1,0
  4453.7    0.05       0  4984.9    0.05       0  4998.3    0.05       0
Bank Sta=4984.9,4998.3
Exp/Cntr=0.3,0.1

Chan Stop Cuts=-1