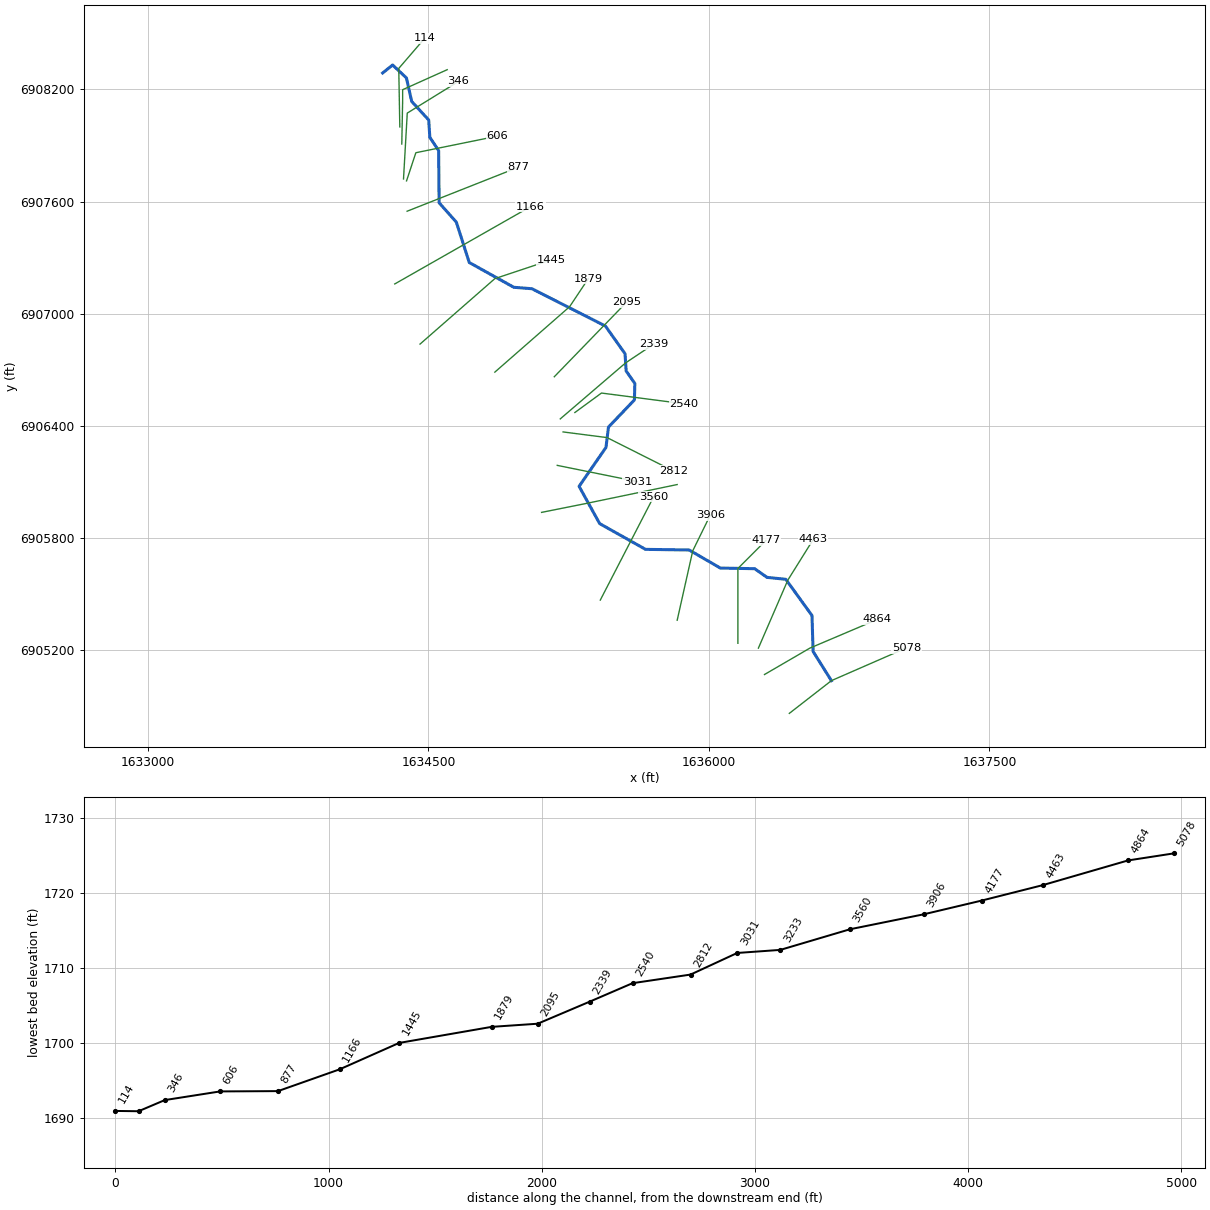
--- Deadman 41.prj (project) ---

Proj Title=Deadman 41 Base Level Engineering
Current Plan=p01
Default Exp/Contr=0.3,0.1
English Units
Geom File=g01
Flow File=f01
Plan File=p01
BEGIN DESCRIPTION:
Deadman 41
END DESCRIPTION:

--- Deadman 41.p01 (plan) ---

Plan Title=Multiple Run
Short Identifier=Multiple
Geom File=g01
Flow File=f01
Subcritical Flow
K Sum by GR= 0
Std Step Tol= 0.01
Critical Tol= 0.01
Num of Std Step Trials= 20
Max Error Tol= 0.3
Flow Tol Ratio= 0.001
Split Flow NTrial= 30
Split Flow Tol= 0.02
Split Flow Ratio= 0.02
Log Output Level= 0
Friction Slope Method= 1
Unsteady Friction Slope Method= 2
Unsteady Bridges Friction Slope Method= 1
Parabolic Critical Depth
Global Vel Dist=  1 , 1 , 1
Global Log Level= 0
CheckData=True
Encroach Param= -1, 0, 0, 0
BEGIN DESCRIPTION:
Multiple Run
END DESCRIPTION:

--- Deadman 41.f01 (steady flow) ---

Flow Title=Multiple
Number of Profiles=7
Profile Names=10-year,25-year,50-year,1pct_min,100-year,1pct_plu,500-year
River Rch & RM= Deadman 41,Reach-1,5078
     213     290     354     215     429     855     637
River Rch & RM= Deadman 41,Reach-1,4864
     275     382     470     288     575    1147     871
Boundary for River Rch & Prof#=Deadman 41,Reach-1,1
Up Type=0
Dn Type=3
Dn Slope=0.007
Boundary for River Rch & Prof#=Deadman 41,Reach-1,2
Up Type=0
Dn Type=3
Dn Slope=0.007
Boundary for River Rch & Prof#=Deadman 41,Reach-1,3
Up Type=0
Dn Type=3
Dn Slope=0.007
Boundary for River Rch & Prof#=Deadman 41,Reach-1,4
Up Type=0
Dn Type=3
Dn Slope=0.007
Boundary for River Rch & Prof#=Deadman 41,Reach-1,5
Up Type=0
Dn Type=3
Dn Slope=0.007
Boundary for River Rch & Prof#=Deadman 41,Reach-1,6
Up Type=0
Dn Type=3
Dn Slope=0.007
Boundary for River Rch & Prof#=Deadman 41,Reach-1,7
Up Type=0
Dn Type=3
Dn Slope=0.007

--- Deadman 41.g01 (geometry) ---

Geom Title=Existing Conditions

River Reach=Deadman 41,Reach-1
Reach XY= 30
      1636655.00      6905038.00      1636557.23      6905193.92
      1636551.25      6905386.45      1636411.19      6905580.15
      1636310.98      6905590.36      1636244.50      6905636.78
      1636060.93      6905640.24      1635894.50      6905736.80
      1635660.93      6905740.24      1635415.65      6905878.00
      1635305.70      6906077.30      1635449.46      6906285.58
      1635462.86      6906394.17      1635601.54      6906539.50
      1635603.90      6906627.45      1635557.36      6906693.98
      1635551.38      6906786.50      1635446.52      6906934.49
      1635053.42      6907134.17      1634956.58      6907141.83
      1634718.26      6907274.34      1634649.15      6907490.29
      1634557.06      6907593.86      1634554.48      6907872.78
      1634507.36      6907943.98      1634501.38      6908036.50
      1634410.54      6908135.58      1634382.13      6908261.62
      1634308.35      6908330.76      1634255.00      6908288.00

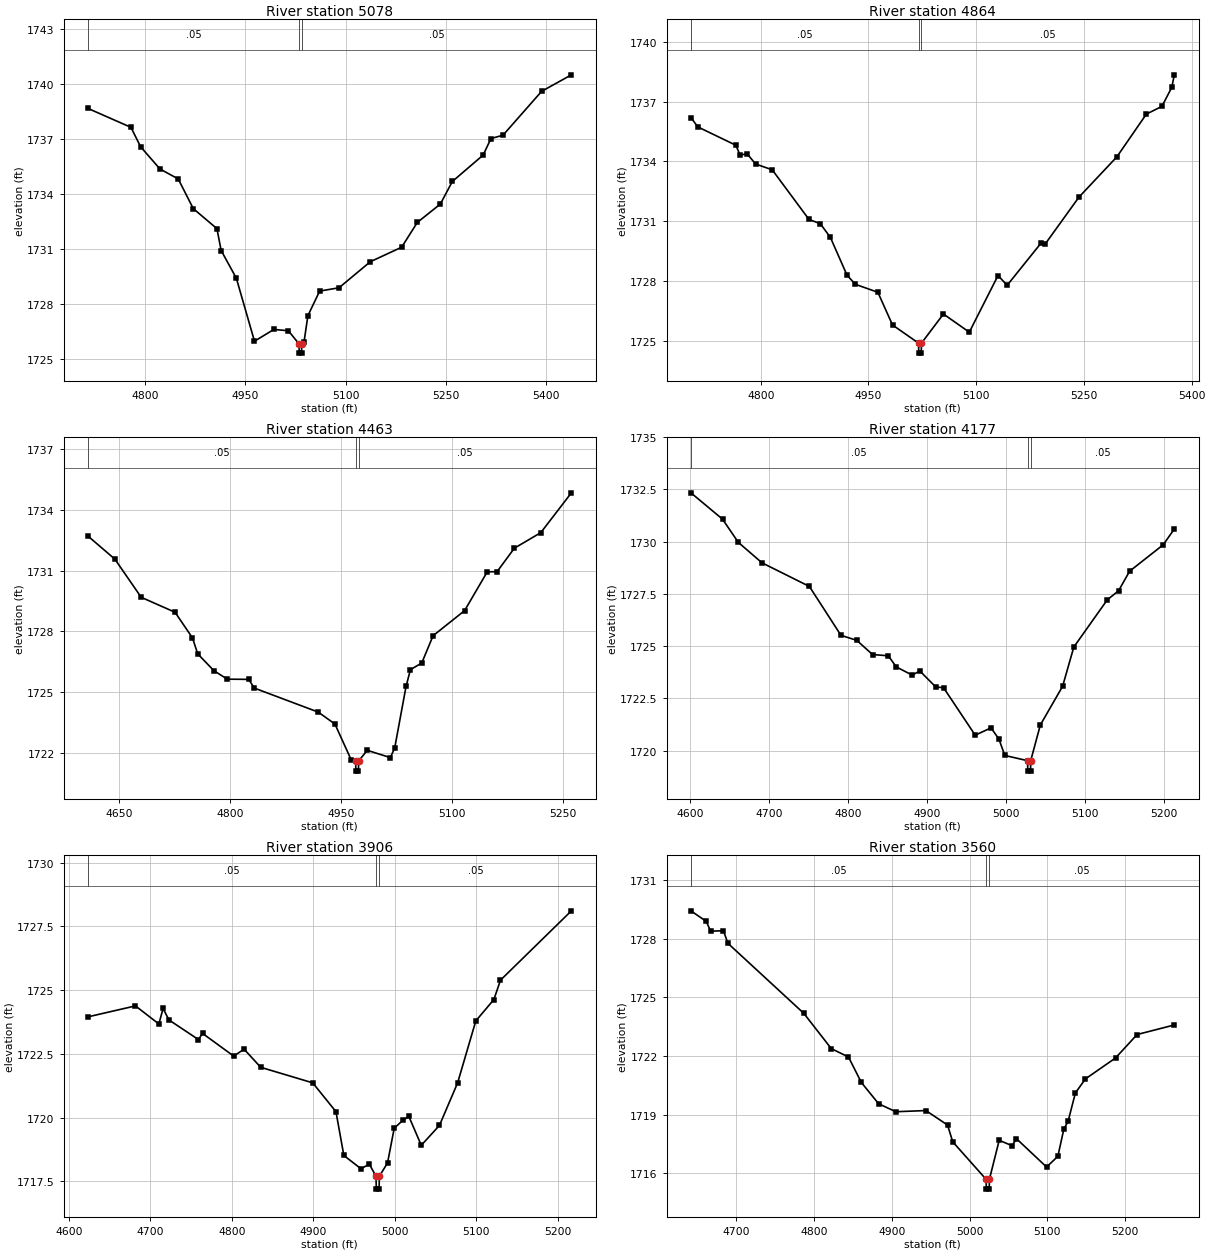
Type RM Length L Ch R = 1,5078,214,214,214
BEGIN DESCRIPTION:
Deadman 41 8.0
END DESCRIPTION:
XS GIS Cut Line= 3
      1636430.03      6904863.03      1636655.00      6905038.00
      1637055.75      6905213.01
#Sta/Elev= 30
  4715.0 1738.66  4779.2 1737.63  4793.7 1736.57  4822.6 1735.36  4849.8 1734.82
  4872.4 1733.20  4907.7 1732.11  4914.0 1730.92  4936.7 1729.41  4963.8 1725.98
  4992.8 1726.62  5014.4 1726.55  5030.4 1725.83  5030.6 1725.33  5034.1 1725.33
  5034.4 1725.83  5037.8 1725.93  5043.6 1727.37  5061.2 1728.71  5090.1 1728.89
  5136.9 1730.31  5183.7 1731.10  5207.1 1732.45  5241.5 1733.45  5259.4 1734.68
  5305.5 1736.12  5317.1 1737.02  5335.1 1737.20  5392.8 1739.59  5437.3 1740.49
#Mann=3,-1,0
  4715.0    0.05       0  5030.4    0.05       0  5034.4    0.05       0
Bank Sta=5030.4,5034.4
Exp/Cntr=0.3,0.1

Type RM Length L Ch R = 1,4864,401,401,401
BEGIN DESCRIPTION:
Mapping XS 4ad93bf3
END DESCRIPTION:
XS GIS Cut Line= 3
      1636297.19      6905070.76      1636539.77      6905211.97
      1636900.93      6905365.46
#Sta/Elev= 30
  4702.8 1736.20  4712.4 1735.73  4765.4 1734.81  4771.2 1734.32  4781.1 1734.38
  4792.8 1733.87  4816.0 1733.58  4867.2 1731.09  4882.9 1730.88  4897.0 1730.19
  4920.1 1728.30  4931.7 1727.84  4963.1 1727.44  4983.5 1725.80  5019.8 1724.89
  5020.0 1724.39  5023.5 1724.39  5023.8 1724.89  5054.4 1726.35  5090.4 1725.44
  5130.4 1728.28  5143.1 1727.79  5190.4 1729.91  5195.9 1729.85  5243.1 1732.21
  5295.9 1734.23  5336.9 1736.37  5358.6 1736.76  5372.3 1737.71  5375.9 1738.34
#Mann=3,-1,0
  4702.8    0.05       0  5019.8    0.03       0  5023.8    0.05       0
Bank Sta=5019.8,5023.8
Exp/Cntr=0.3,0.1

Type RM Length L Ch R = 1,4463,286,286,286
BEGIN DESCRIPTION:
Mapping XS 3a7c4269
END DESCRIPTION:
XS GIS Cut Line= 3
      1636264.61      6905211.99      1636422.10      6905575.86
      1636557.84      6905793.04
#Sta/Elev= 30
  4608.5 1732.71  4644.8 1731.57  4680.4 1729.68  4726.1 1728.94  4749.6 1727.67
  4756.7 1726.88  4778.5 1726.05  4796.6 1725.63  4825.5 1725.62  4833.0 1725.19
  4919.4 1724.00  4941.9 1723.41  4963.7 1721.65  4969.9 1721.58  4970.1 1721.08
  4973.6 1721.08  4973.9 1721.58  4985.5 1722.11  5016.6 1721.75  5022.5 1722.21
  5037.9 1725.27  5043.8 1726.10  5059.1 1726.43  5074.4 1727.78  5116.9 1729.02
  5147.5 1730.94  5160.8 1730.95  5184.1 1732.11  5219.8 1732.88  5261.1 1734.85
#Mann=3,-1,0
  4608.5    0.05       0  4969.9    0.05       0  4973.9    0.05       0
Bank Sta=4969.9,4973.9
Exp/Cntr=0.3,0.1

Type RM Length L Ch R = 1,4177,271,271,271
BEGIN DESCRIPTION:
Deadman 41 7.0
END DESCRIPTION:
XS GIS Cut Line= 3
      1636155.00      6905237.96      1636155.00      6905638.00
      1636305.02      6905788.02
#Sta/Elev= 30
  4600.7 1732.34  4640.7 1731.08  4660.7 1729.97  4690.7 1728.99  4750.7 1727.86
  4790.7 1725.52  4810.7 1725.28  4830.7 1724.60  4850.7 1724.54  4860.7 1724.01
  4880.7 1723.62  4890.7 1723.81  4910.7 1723.05  4920.7 1723.01  4960.7 1720.74
  4980.7 1721.09  4990.7 1720.56  4998.2 1719.77  5027.0 1719.52  5027.3 1719.02
  5030.8 1719.02  5031.0 1719.52  5043.2 1721.23  5071.4 1723.08  5085.6 1724.96
  5128.0 1727.22  5142.2 1727.65  5156.3 1728.59  5198.7 1729.85  5212.9 1730.61
#Mann=3,-1,0
  4600.7    0.05       0  5027.0    0.03       0  5031.0    0.05       0
Bank Sta=5027,5031
Exp/Cntr=0.3,0.1

Type RM Length L Ch R = 1,3906,346,346,346
BEGIN DESCRIPTION:
Mapping XS ff0ccbf4
END DESCRIPTION:
XS GIS Cut Line= 3
      1635830.28      6905361.09      1635913.61      6905732.64
      1636007.22      6905923.32
#Sta/Elev= 30
  4623.4 1723.95  4681.7 1724.38  4710.4 1723.67  4715.6 1724.28  4722.7 1723.83
  4758.9 1723.06  4764.0 1723.30  4802.2 1722.41  4815.0 1722.68  4835.4 1721.97
  4899.2 1721.36  4927.7 1720.23  4937.4 1718.51  4958.4 1717.99  4968.7 1718.17
  4976.9 1717.69  4977.2 1717.19  4980.7 1717.19  4980.9 1717.69  4991.0 1718.22
  4999.2 1719.58  5010.1 1719.90  5017.2 1720.04  5032.4 1718.91  5054.7 1719.69
  5077.0 1721.36  5099.3 1723.79  5121.5 1724.63  5129.6 1725.39  5216.6 1728.11
#Mann=3,-1,0
  4623.4    0.05       0  4976.9    0.03       0  4980.9    0.05       0
Bank Sta=4976.9,4980.9
Exp/Cntr=0.3,0.1

Type RM Length L Ch R = 1,3560,327,327,327
BEGIN DESCRIPTION:
Mapping XS 9f0a6c04
END DESCRIPTION:
XS GIS Cut Line= 2
      1635419.13      6905469.04      1635704.29      6906021.04
#Sta/Elev= 30
  4641.9 1729.43  4661.6 1728.89  4667.2 1728.39  4683.7 1728.41  4689.4 1727.77
  4787.1 1724.18  4822.3 1722.38  4844.4 1721.95  4860.9 1720.65  4883.1 1719.56
  4905.2 1719.15  4943.9 1719.21  4971.7 1718.47  4978.4 1717.61  5021.3 1715.69
  5021.6 1715.19  5025.3 1715.19  5025.5 1715.69  5038.1 1717.69  5054.7 1717.41
  5060.3 1717.77  5099.0 1716.32  5113.5 1716.87  5121.1 1718.25  5126.7 1718.67
  5136.0 1720.11  5148.9 1720.83  5187.6 1721.90  5215.3 1723.10  5263.2 1723.59
#Mann=3,-1,0
  4641.9    0.05       0  5021.3    0.03       0  5025.5    0.05       0
Bank Sta=5021.3,5025.5
Exp/Cntr=0.3,0.1

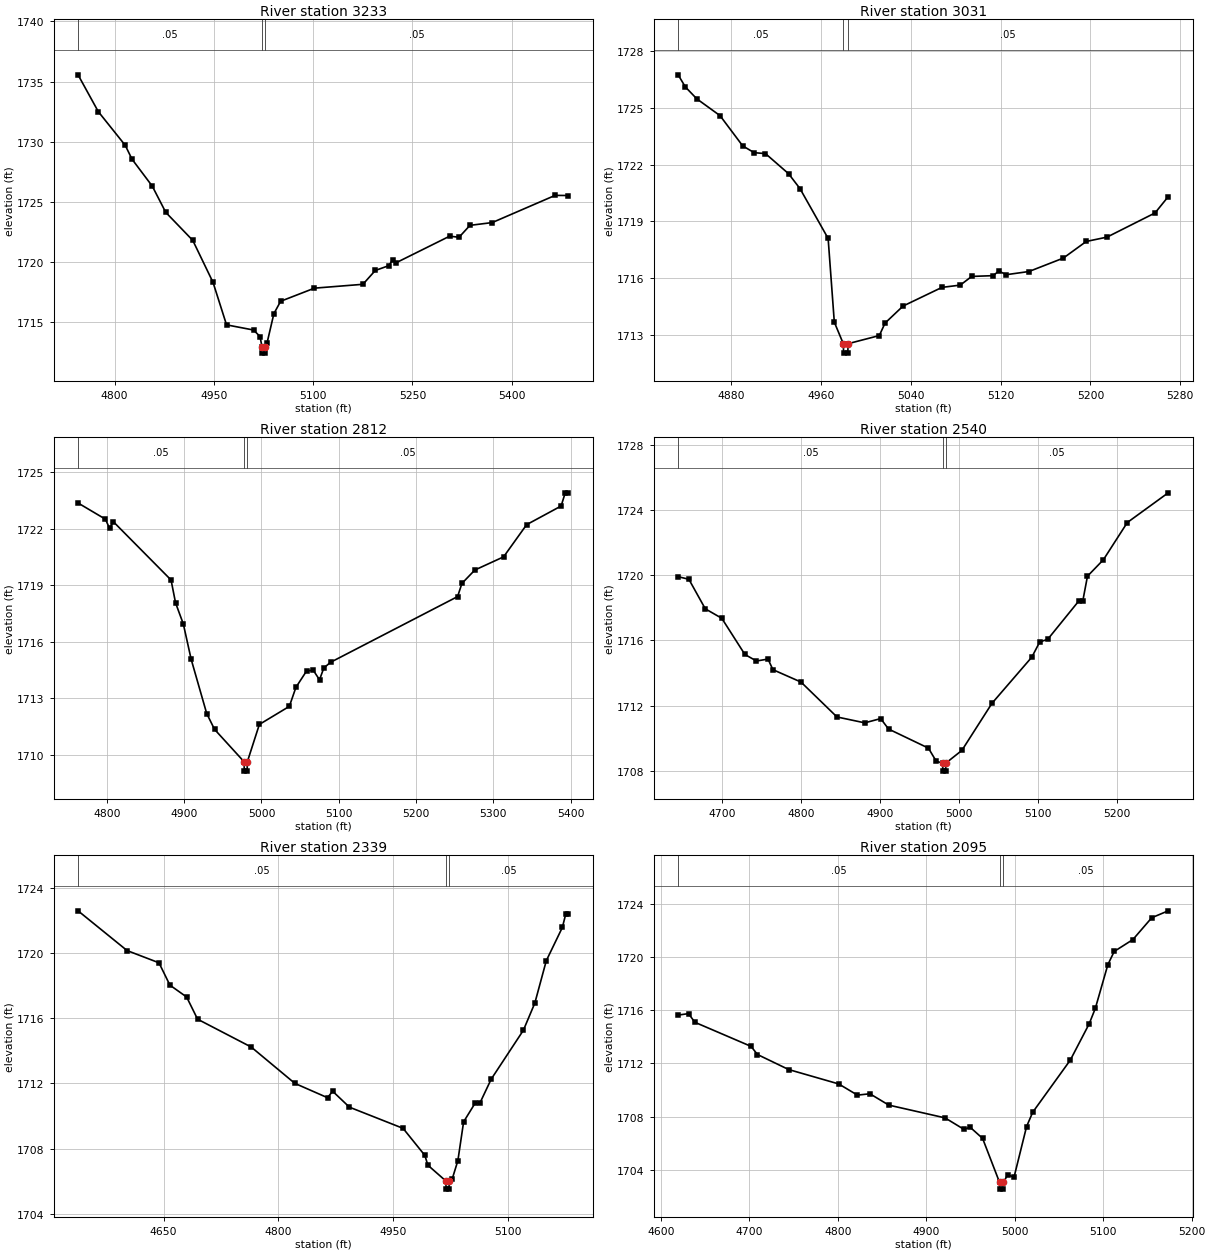
Type RM Length L Ch R = 1,3233,202,202,202
BEGIN DESCRIPTION:
Deadman 41 6.0
END DESCRIPTION:
XS GIS Cut Line= 3
      1635105.04      6905938.01      1635355.00      6905988.00
      1635830.13      6906086.77
#Sta/Elev= 30
  4744.9 1735.56  4775.5 1732.50  4816.2 1729.70  4826.4 1728.55  4857.0 1726.31
  4877.4 1724.13  4918.2 1721.80  4948.8 1718.31  4969.2 1714.78  5010.0 1714.35
  5019.8 1713.81  5022.8 1712.93  5023.0 1712.43  5026.7 1712.43  5027.0 1712.93
  5030.5 1713.30  5040.7 1715.71  5050.9 1716.74  5102.0 1717.83  5175.2 1718.15
  5193.9 1719.30  5214.3 1719.70  5220.2 1720.19  5225.3 1719.94  5306.2 1722.15
  5320.4 1722.06  5336.9 1723.05  5370.5 1723.28  5465.5 1725.54  5485.1 1725.53
#Mann=3,-1,0
  4744.9    0.05       0  5022.8    0.03       0  5027.0    0.05       0
Bank Sta=5022.8,5027
Exp/Cntr=0.3,0.1

Type RM Length L Ch R = 1,3031,219,219,219
BEGIN DESCRIPTION:
Mapping XS f7bbf38a
END DESCRIPTION:
XS GIS Cut Line= 2
      1635188.69      6906189.42      1635616.51      6906102.82
#Sta/Elev= 30
  4832.7 1726.75  4839.1 1726.11  4849.3 1725.48  4870.0 1724.59  4890.2 1722.99
  4900.4 1722.63  4910.5 1722.58  4931.0 1721.52  4941.2 1720.73  4966.3 1718.09
  4971.8 1713.66  4979.8 1712.52  4980.1 1712.02  4983.8 1712.02  4984.1 1712.52
  5011.9 1712.95  5017.0 1713.61  5033.0 1714.51  5067.7 1715.50  5084.0 1715.62
  5094.2 1716.08  5113.3 1716.12  5118.4 1716.37  5124.8 1716.17  5145.2 1716.34
  5175.8 1717.05  5196.2 1717.93  5214.7 1718.16  5257.5 1719.44  5269.2 1720.30
#Mann=3,-1,0
  4832.7    0.05       0  4979.8    0.03       0  4984.1    0.05       0
Bank Sta=4979.8,4984.1
Exp/Cntr=0.3,0.1

Type RM Length L Ch R = 1,2812,272,272,272
BEGIN DESCRIPTION:
Deadman 41 5.0
END DESCRIPTION:
XS GIS Cut Line= 3
      1635219.93      6906368.24      1635455.00      6906338.00
      1635809.48      6906159.71
#Sta/Elev= 30
  4762.8 1723.37  4798.2 1722.51  4803.5 1722.03  4808.6 1722.37  4883.1 1719.28
  4888.9 1718.07  4899.0 1716.94  4909.1 1715.07  4929.2 1712.19  4939.3 1711.35
  4977.5 1709.63  4977.8 1709.13  4981.5 1709.13  4981.8 1709.63  4997.3 1711.61
  5036.1 1712.57  5044.6 1713.58  5058.4 1714.45  5067.0 1714.49  5075.1 1713.98
  5080.7 1714.61  5089.4 1714.91  5253.7 1718.40  5259.3 1719.10  5276.0 1719.81
  5313.2 1720.51  5343.0 1722.22  5387.6 1723.21  5392.9 1723.91  5396.6 1723.91
#Mann=3,-1,0
  4762.8    0.05       0  4977.5    0.03       0  4981.8    0.05       0
Bank Sta=4977.5,4981.8
Exp/Cntr=0.3,0.1

Type RM Length L Ch R = 1,2540,201,201,201
BEGIN DESCRIPTION:
Mapping XS b5d1f931
END DESCRIPTION:
XS GIS Cut Line= 3
      1635283.06      6906472.04      1635425.45      6906576.22
      1635866.41      6906518.93
#Sta/Elev= 30
  4644.0 1719.90  4657.6 1719.74  4678.4 1717.93  4699.3 1717.35  4728.6 1715.13
  4743.3 1714.73  4757.9 1714.85  4764.1 1714.20  4799.7 1713.44  4845.3 1711.30
  4880.5 1710.94  4900.7 1711.20  4910.7 1710.56  4961.2 1709.39  4971.2 1708.58
  4979.2 1708.48  4979.5 1707.98  4983.2 1707.98  4983.5 1708.48  5003.6 1709.25
  5041.8 1712.14  5092.3 1714.97  5102.3 1715.90  5112.4 1716.06  5151.8 1718.41
  5156.9 1718.42  5162.8 1719.93  5183.0 1720.94  5213.3 1723.22  5265.1 1725.04
#Mann=3,-1,0
  4644.0    0.05       0  4979.2    0.05       0  4983.5    0.05       0
Bank Sta=4979.2,4983.5
Exp/Cntr=0.3,0.1

Type RM Length L Ch R = 1,2339,244,244,244
BEGIN DESCRIPTION:
Deadman 41 4.0
END DESCRIPTION:
XS GIS Cut Line= 3
      1635205.01      6906438.01      1635555.00      6906738.00
      1635704.96      6906837.98
#Sta/Elev= 30
  4538.0 1722.59  4602.2 1720.15  4643.9 1719.40  4658.2 1718.03  4680.1 1717.30
  4694.4 1715.94  4764.6 1714.23  4821.7 1712.00  4864.5 1711.12  4871.1 1711.52
  4893.1 1710.54  4963.3 1709.24  4991.8 1707.58  4995.7 1706.98  5019.3 1706.01
  5019.6 1705.51  5023.4 1705.51  5023.7 1706.01  5027.5 1706.12  5035.0 1707.26
  5042.5 1709.64  5057.6 1710.79  5063.6 1710.77  5078.6 1712.26  5120.7 1715.26
  5135.7 1716.93  5150.7 1719.53  5171.7 1721.57  5176.2 1722.40  5179.2 1722.40
#Mann=3,-1,0
  4538.0    0.05       0  5019.3    0.05       0  5023.7    0.05       0
Bank Sta=5019.3,5023.7
Exp/Cntr=0.3,0.1

Type RM Length L Ch R = 1,2095,216,216,216
BEGIN DESCRIPTION:
Mapping XS 92ea168c
END DESCRIPTION:
XS GIS Cut Line= 2
      1635173.05      6906663.40      1635558.45      6907060.96
#Sta/Elev= 30
  4619.7 1715.63  4631.4 1715.74  4638.6 1715.09  4702.1 1713.28  4709.3 1712.67
  4744.6 1711.54  4801.1 1710.46  4822.3 1709.62  4836.4 1709.72  4857.7 1708.87
  4921.3 1707.91  4942.6 1707.05  4949.6 1707.21  4963.7 1706.37  4982.9 1703.06
  4983.2 1702.56  4987.0 1702.56  4987.3 1703.06  4992.0 1703.64  4999.2 1703.45
  5013.4 1707.26  5020.3 1708.33  5062.8 1712.25  5084.1 1714.97  5091.1 1716.14
  5105.2 1719.41  5112.4 1720.41  5133.5 1721.30  5154.8 1722.94  5173.4 1723.46
#Mann=3,-1,0
  4619.7    0.05       0  4982.9    0.05       0  4987.3    0.05       0
Bank Sta=4982.9,4987.3
Exp/Cntr=0.3,0.1

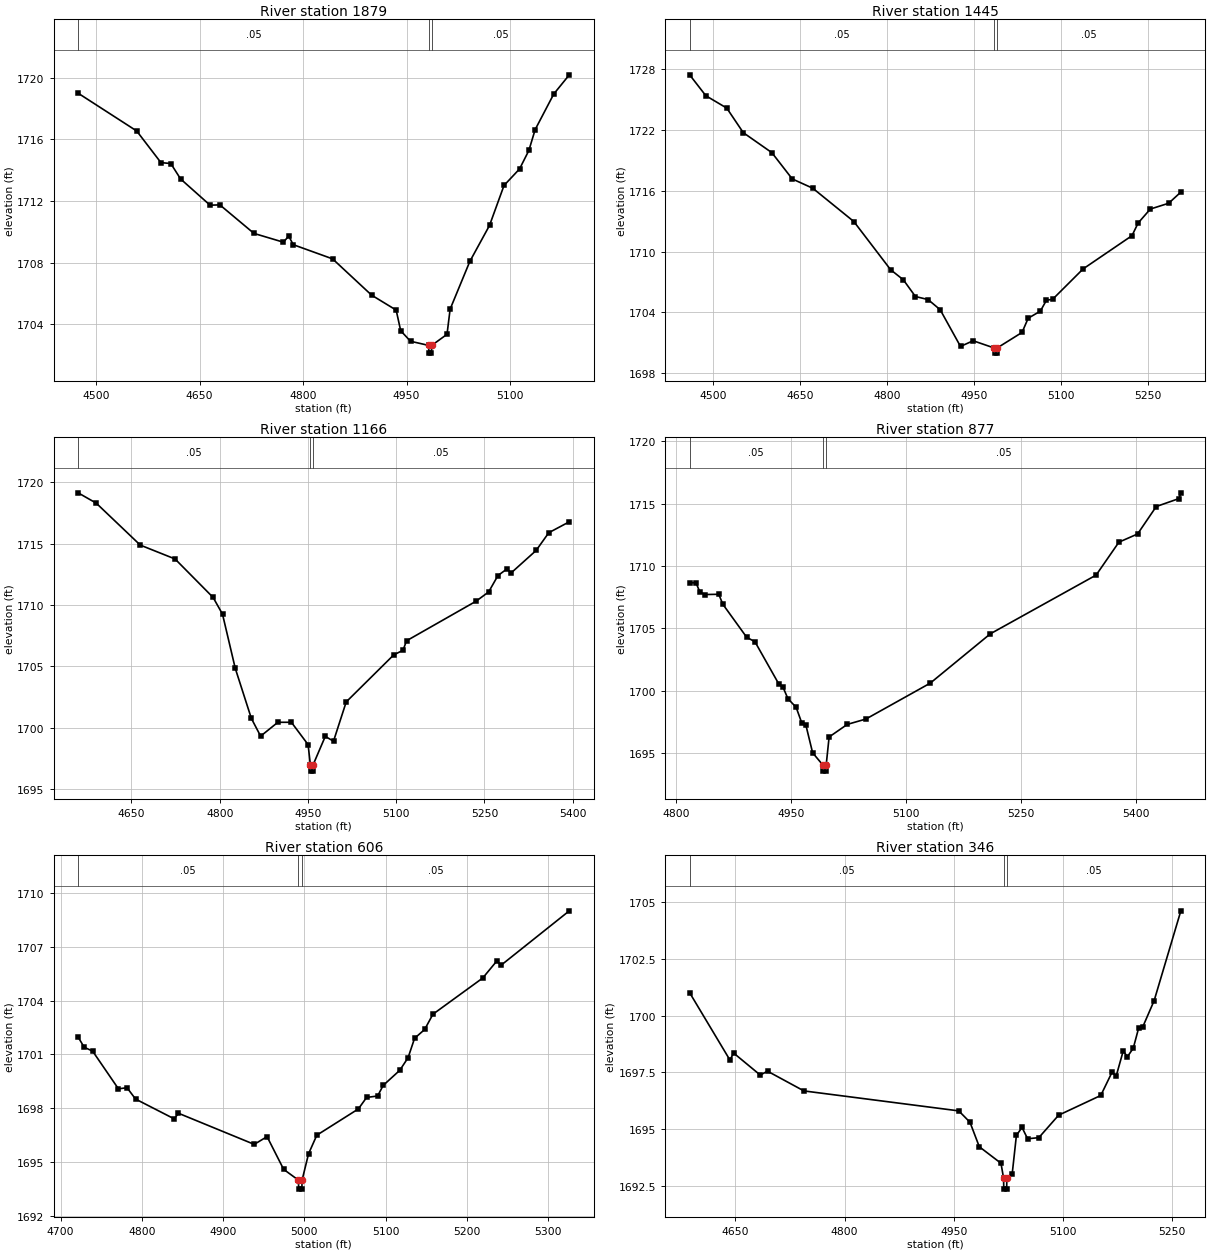
Type RM Length L Ch R = 1,1879,434,434,434
BEGIN DESCRIPTION:
Deadman 41 3.0
END DESCRIPTION:
XS GIS Cut Line= 3
      1634855.04      6906688.03      1635255.00      6907038.00
      1635354.98      6907187.97
#Sta/Elev= 30
  4474.1 1718.99  4559.0 1716.54  4594.1 1714.49  4608.4 1714.43  4622.6 1713.43
  4665.3 1711.73  4679.5 1711.75  4728.9 1709.90  4771.6 1709.33  4779.2 1709.73
  4785.8 1709.17  4842.8 1708.25  4899.3 1705.90  4934.9 1704.93  4941.5 1703.59
  4955.7 1702.91  4982.0 1702.64  4982.3 1702.14  4986.1 1702.14  4986.4 1702.64
  5008.6 1703.36  5013.1 1704.99  5041.6 1708.08  5070.2 1710.42  5091.2 1713.01
  5113.7 1714.08  5127.2 1715.28  5136.3 1716.63  5163.3 1718.94  5185.8 1720.18
#Mann=3,-1,0
  4474.1    0.05       0  4982.0    0.05       0  4986.4    0.05       0
Bank Sta=4982,4986.4
Exp/Cntr=0.3,0.1

Type RM Length L Ch R = 1,1445,279,279,279
BEGIN DESCRIPTION:
Deadman 41 2.0
END DESCRIPTION:
XS GIS Cut Line= 3
      1634454.97      6906837.97      1634855.00      6907188.00
      1635155.02      6907288.01
#Sta/Elev= 30
  4459.6 1727.42  4487.6 1725.36  4523.7 1724.14  4552.2 1721.72  4601.5 1719.75
  4636.7 1717.16  4672.2 1716.24  4743.0 1712.96  4806.5 1708.21  4828.4 1707.22
  4849.3 1705.57  4871.1 1705.27  4892.0 1704.27  4927.1 1700.65  4948.9 1701.21
  4985.6 1700.49  4985.9 1699.99  4989.8 1699.99  4990.1 1700.49  5033.3 1702.03
  5043.9 1703.43  5064.9 1704.13  5075.5 1705.21  5086.0 1705.29  5138.7 1708.29
  5223.1 1711.57  5233.6 1712.81  5254.7 1714.19  5286.3 1714.76  5307.4 1715.86
#Mann=3,-1,0
  4459.6    0.05       0  4985.6    0.03       0  4990.1    0.05       0
Bank Sta=4985.6,4990.1
Exp/Cntr=0.3,0.1

Type RM Length L Ch R = 1,1166,289,289,289
BEGIN DESCRIPTION:
Mapping XS 0e36f4f5
END DESCRIPTION:
XS GIS Cut Line= 2
      1634319.87      6907159.72      1635045.58      6907572.93
#Sta/Elev= 30
  4559.3 1719.14  4590.1 1718.30  4665.0 1714.88  4724.1 1713.75  4788.9 1710.61
  4804.8 1709.25  4826.4 1704.85  4853.8 1700.76  4869.6 1699.31  4898.9 1700.44
  4921.9 1700.44  4950.3 1698.62  4954.2 1696.96  4954.5 1696.46  4958.4 1696.46
  4958.7 1696.96  4979.5 1699.29  4993.5 1698.90  5015.1 1702.10  5095.8 1705.93
  5111.7 1706.31  5117.6 1707.08  5235.6 1710.30  5257.2 1711.06  5273.1 1712.40
  5289.0 1712.96  5294.7 1712.58  5337.9 1714.44  5359.5 1715.89  5394.4 1716.78
#Mann=3,-1,0
  4559.3    0.05       0  4954.2    0.03       0  4958.7    0.05       0
Bank Sta=4954.2,4958.7
Exp/Cntr=0.3,0.1

Type RM Length L Ch R = 1,877,271,271,271
BEGIN DESCRIPTION:
Mapping XS a5bf71b8
END DESCRIPTION:
XS GIS Cut Line= 2
      1634385.80      6907548.60      1634981.54      6907784.12
#Sta/Elev= 30
  4817.9 1708.66  4826.1 1708.67  4831.5 1707.89  4838.5 1707.72  4855.9 1707.74
  4861.2 1706.94  4892.3 1704.29  4903.1 1703.93  4934.3 1700.53  4939.7 1700.28
  4946.1 1699.36  4956.8 1698.67  4964.0 1697.44  4969.4 1697.27  4978.3 1695.02
  4991.5 1694.05  4991.8 1693.55  4995.7 1693.55  4996.0 1694.05  4999.8 1696.29
  5023.5 1697.30  5047.8 1697.73  5131.7 1700.61  5210.1 1704.57  5348.0 1709.28
  5377.7 1711.92  5402.1 1712.58  5426.4 1714.78  5456.1 1715.42  5458.5 1715.88
#Mann=3,-1,0
  4817.9    0.05       0  4991.5    0.05       0  4996.0    0.05       0
Bank Sta=4991.5,4996
Exp/Cntr=0.3,0.1

Type RM Length L Ch R = 1,606,260,260,260
BEGIN DESCRIPTION:
Mapping XS bb1c30a1
END DESCRIPTION:
XS GIS Cut Line= 3
      1634382.80      6907710.85      1634432.70      6907861.53
      1634869.42      6907950.38
#Sta/Elev= 30
  4721.6 1701.97  4729.1 1701.40  4739.4 1701.19  4771.2 1699.09  4781.8 1699.15
  4792.3 1698.52  4839.8 1697.42  4845.1 1697.73  4938.3 1696.00  4954.1 1696.43
  4974.5 1694.61  4992.7 1694.01  4993.0 1693.51  4996.9 1693.51  4997.2 1694.01
  5005.1 1695.47  5015.3 1696.51  5066.4 1697.97  5076.6 1698.61  5090.1 1698.69
  5097.0 1699.28  5117.4 1700.12  5127.6 1700.82  5135.6 1701.90  5148.0 1702.39
  5158.2 1703.24  5219.4 1705.25  5236.8 1706.20  5241.9 1705.96  5326.0 1708.99
#Mann=3,-1,0
  4721.6    0.05       0  4992.7    0.03       0  4997.2    0.05       0
Bank Sta=4992.7,4997.2
Exp/Cntr=0.3,0.1

Type RM Length L Ch R = 1,346,123,123,123
BEGIN DESCRIPTION:
Mapping XS 9bde2ed1
END DESCRIPTION:
XS GIS Cut Line= 3
      1634366.66      6907721.21      1634386.66      6908073.43
      1634660.61      6908242.67
#Sta/Elev= 30
  4587.2 1701.01  4642.6 1698.04  4647.6 1698.35  4684.2 1697.38  4694.2 1697.55
  4744.2 1696.68  4956.9 1695.80  4972.3 1695.30  4985.1 1694.22  5014.9 1693.49
  5018.4 1692.85  5018.8 1692.35  5022.7 1692.35  5023.0 1692.85  5030.3 1693.02
  5036.1 1694.72  5043.8 1695.07  5051.5 1694.57  5066.9 1694.62  5094.1 1695.61
  5152.0 1696.48  5167.4 1697.50  5173.3 1697.35  5182.8 1698.44  5188.6 1698.19
  5196.6 1698.56  5204.0 1699.45  5209.9 1699.52  5225.3 1700.66  5262.0 1704.62
#Mann=3,-1,0
  4587.2    0.05       0  5018.4    0.03       0  5023.0    0.05       0
Bank Sta=5018.4,5023
Exp/Cntr=0.3,0.1

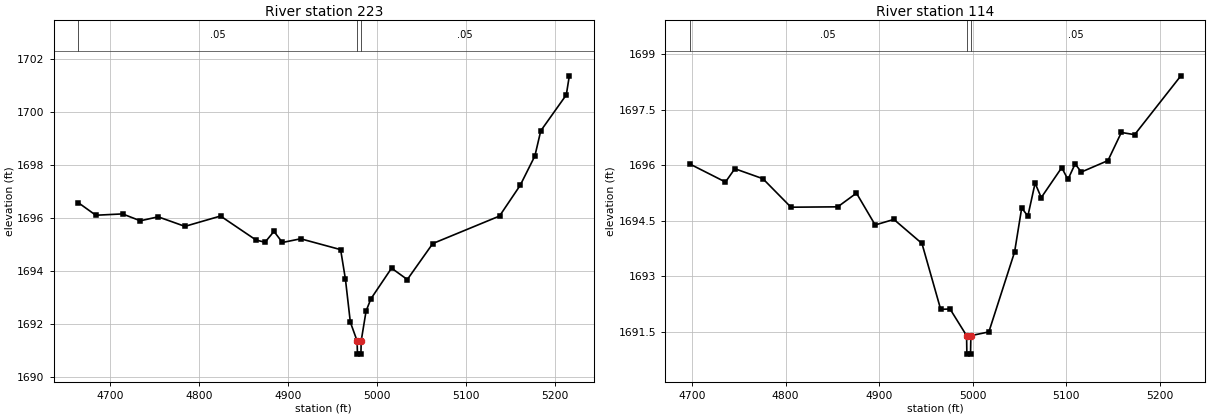
Type RM Length L Ch R = 1,223,109,109,109
BEGIN DESCRIPTION:
Mapping XS f5c07233
END DESCRIPTION:
XS GIS Cut Line= 4
      1634357.44      6907908.07      1634362.05      6908142.09
      1634362.05      6908198.59      1634600.34      6908305.65
#Sta/Elev= 30
  4664.2 1696.59  4684.1 1696.11  4714.1 1696.16  4734.1 1695.90  4754.1 1696.05
  4784.2 1695.69  4824.2 1696.08  4864.2 1695.17  4874.2 1695.09  4884.2 1695.50
  4893.7 1695.08  4914.2 1695.22  4959.1 1694.81  4964.5 1693.69  4970.0 1692.07
  4977.6 1691.36  4978.0 1690.86  4981.9 1690.86  4982.2 1691.36  4987.7 1692.49
  4993.1 1692.95  5016.3 1694.11  5034.0 1693.68  5062.6 1695.04  5137.6 1696.08
  5160.8 1697.24  5177.3 1698.35  5183.9 1699.30  5212.6 1700.66  5216.0 1701.38
#Mann=3,-1,0
  4664.2    0.05       0  4977.6    0.03       0  4982.2    0.05       0
Bank Sta=4977.6,4982.2
Exp/Cntr=0.3,0.1

Type RM Length L Ch R = 1,114,0,0,0
BEGIN DESCRIPTION:
Deadman 41 1.0
END DESCRIPTION:
XS GIS Cut Line= 3
      1634346.80      6907999.75      1634341.25      6908312.43
      1634479.77      6908473.28
#Sta/Elev= 30
  4697.4 1696.04  4735.7 1695.55  4745.7 1695.91  4775.7 1695.64  4805.7 1694.87
  4855.7 1694.88  4875.7 1695.25  4895.7 1694.39  4915.7 1694.54  4945.7 1693.89
  4965.7 1692.11  4975.7 1692.12  4993.4 1691.40  4993.7 1690.90  4997.6 1690.90
  4998.0 1691.40  5017.2 1691.50  5044.7 1693.66  5052.3 1694.85  5058.9 1694.63
  5066.6 1695.52  5073.2 1695.13  5095.1 1695.94  5101.7 1695.62  5109.4 1696.04
  5116.0 1695.82  5144.5 1696.13  5158.8 1696.89  5173.0 1696.83  5222.4 1698.42
#Mann=3,-1,0
  4697.4    0.05       0  4993.4    0.03       0  4998.0    0.05       0
Bank Sta=4993.4,4998
Exp/Cntr=0.3,0.1

Chan Stop Cuts=-1