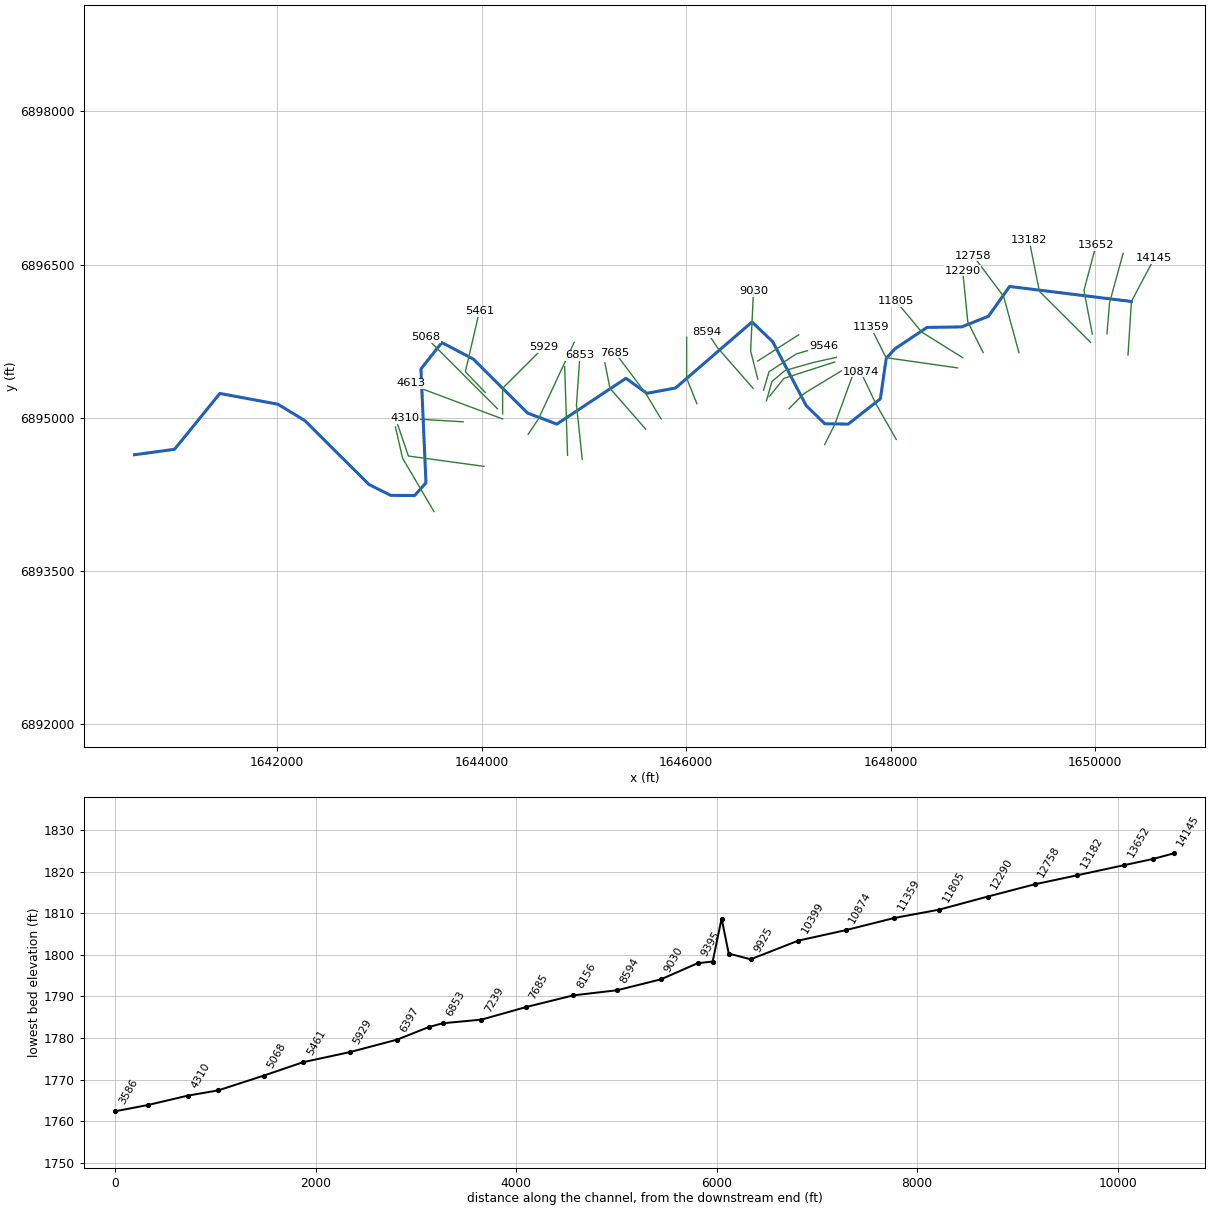
--- Deadman 42.prj (project) ---

Proj Title=Deadman 42 Base Level Engineering
Current Plan=p01
Default Exp/Contr=0.3,0.1
English Units
Geom File=g01
Flow File=f01
Plan File=p01
BEGIN DESCRIPTION:
Deadman 42
END DESCRIPTION:

--- Deadman 42.p01 (plan) ---

Plan Title=Multiple Run
Short Identifier=Multiple
Geom File=g01
Flow File=f01
Subcritical Flow
K Sum by GR= 0
Std Step Tol= 0.01
Critical Tol= 0.01
Num of Std Step Trials= 20
Max Error Tol= 0.3
Flow Tol Ratio= 0.001
Split Flow NTrial= 30
Split Flow Tol= 0.02
Split Flow Ratio= 0.02
Log Output Level= 0
Friction Slope Method= 1
Unsteady Friction Slope Method= 2
Unsteady Bridges Friction Slope Method= 1
Parabolic Critical Depth
Global Vel Dist=  1 , 1 , 1
Global Log Level= 0
CheckData=True
Encroach Param= -1, 0, 0, 0
BEGIN DESCRIPTION:
Multiple Run
END DESCRIPTION:

--- Deadman 42.f01 (steady flow) ---

Flow Title=Multiple
Number of Profiles=7
Profile Names=10-year,25-year,50-year,1pct_min,100-year,1pct_plu,500-year
River Rch & RM= Deadman 42,Reach-1,14145
     212     290     353     214     427     853     635
River Rch & RM= Deadman 42,Reach-1,13935
     328     458     566     348     694    1384    1056
River Rch & RM= Deadman 42,Reach-1,4613
     382     537     667     412     822    1641    1265
Boundary for River Rch & Prof#=Deadman 42,Reach-1,1
Up Type=0
Dn Type=3
Dn Slope=0.01
Boundary for River Rch & Prof#=Deadman 42,Reach-1,2
Up Type=0
Dn Type=3
Dn Slope=0.01
Boundary for River Rch & Prof#=Deadman 42,Reach-1,3
Up Type=0
Dn Type=3
Dn Slope=0.01
Boundary for River Rch & Prof#=Deadman 42,Reach-1,4
Up Type=0
Dn Type=3
Dn Slope=0.01
Boundary for River Rch & Prof#=Deadman 42,Reach-1,5
Up Type=0
Dn Type=3
Dn Slope=0.01
Boundary for River Rch & Prof#=Deadman 42,Reach-1,6
Up Type=0
Dn Type=3
Dn Slope=0.01
Boundary for River Rch & Prof#=Deadman 42,Reach-1,7
Up Type=0
Dn Type=3
Dn Slope=0.01

--- Deadman 42.g01 (geometry) ---

Geom Title=Existing Conditions

River Reach=Deadman 42,Reach-1
Reach XY= 30
      1650355.00      6896138.00      1649163.30      6896284.94
      1648957.31      6895993.82      1648694.50      6895889.22
      1648356.46      6895884.46      1648041.67      6895674.61
      1647957.05      6895582.16      1647899.53      6895185.55
      1647585.02      6894937.96      1647356.46      6894941.54
      1647174.63      6895117.85      1646846.86      6895744.06
      1646644.38      6895937.41      1645896.56      6895291.41
      1645615.53      6895239.08      1645411.16      6895386.25
      1644734.95      6894937.79      1644448.94      6895046.14
      1643918.21      6895574.37      1643610.89      6895736.04
      1643406.20      6895477.50      1643455.30      6894362.87
      1643344.57      6894239.04      1643110.93      6894240.24
      1642898.94      6894346.14      1642271.68      6894971.36
      1642007.45      6895132.53      1641439.58      6895237.97
      1640996.52      6894691.46      1640605.00      6894638.00

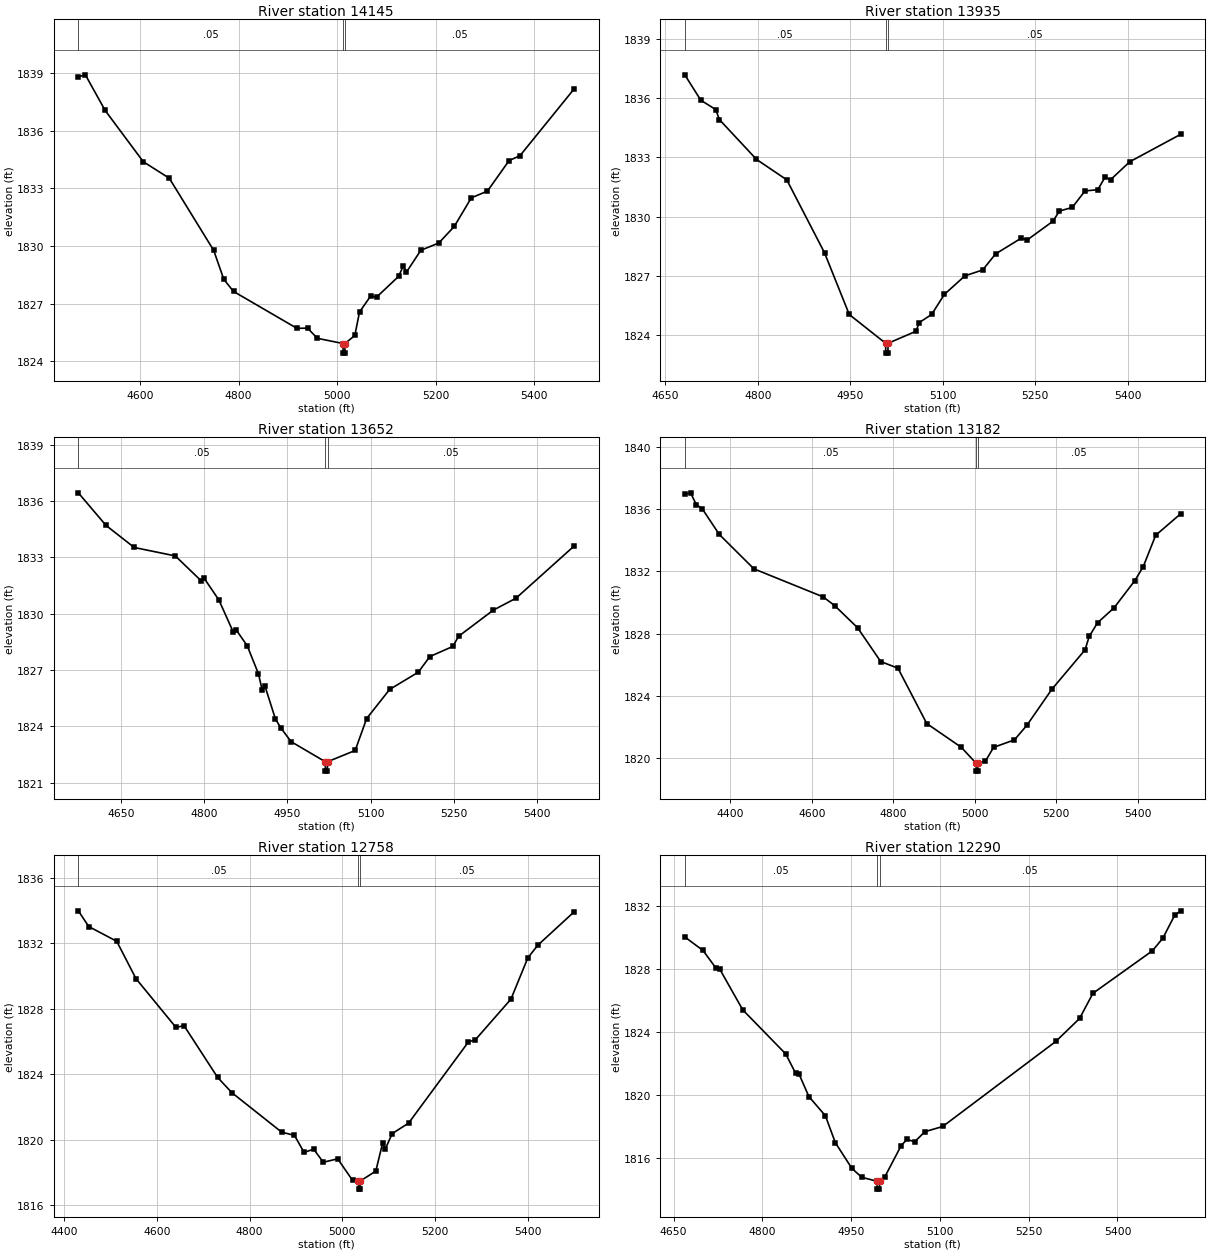
Type RM Length L Ch R = 1,14145,210,210,210
BEGIN DESCRIPTION:
Deadman 42 26.0
END DESCRIPTION:
XS GIS Cut Line= 3
      1650321.43      6895613.77      1650355.00      6896138.00
      1650580.01      6896563.01
#Sta/Elev= 30
  4474.7 1838.81  4489.0 1838.91  4529.0 1837.06  4606.5 1834.39  4659.3 1833.53
  4749.5 1829.77  4769.9 1828.27  4789.6 1827.64  4918.3 1825.72  4939.9 1825.73
  4959.9 1825.20  5011.8 1824.93  5012.1 1824.43  5015.6 1824.43  5015.8 1824.93
  5035.8 1825.35  5045.3 1826.57  5067.9 1827.40  5079.8 1827.34  5124.5 1828.42
  5134.5 1828.98  5140.2 1828.63  5169.7 1829.78  5206.2 1830.16  5237.6 1831.02
  5272.2 1832.51  5304.9 1832.86  5348.9 1834.45  5370.9 1834.70  5480.9 1838.18
#Mann=3,-1,0
  4474.7    0.05       0  5011.8    0.03       0  5015.8    0.05       0
Bank Sta=5011.8,5015.8
Exp/Cntr=0.3,0.1

Type RM Length L Ch R = 1,13935,283,283,283
BEGIN DESCRIPTION:
Mapping XS b10fc9cc
END DESCRIPTION:
XS GIS Cut Line= 3
      1650115.91      6895822.09      1650141.25      6896126.12
      1650273.58      6896607.58
#Sta/Elev= 30
  4681.5 1837.19  4707.5 1835.90  4731.6 1835.43  4737.6 1834.92  4797.8 1832.90
  4847.0 1831.86  4908.2 1828.16  4948.3 1825.03  5007.3 1823.57  5007.5 1823.07
  5011.0 1823.07  5011.3 1823.57  5056.6 1824.18  5061.8 1824.62  5081.9 1825.03
  5102.6 1826.05  5135.9 1826.99  5164.8 1827.29  5185.6 1828.10  5227.1 1828.90
  5237.4 1828.82  5278.7 1829.76  5289.3 1830.28  5310.0 1830.46  5330.8 1831.30
  5351.5 1831.36  5363.1 1831.99  5372.3 1831.87  5403.4 1832.78  5485.9 1834.17
#Mann=3,-1,0
  4681.5    0.05       0  5007.3    0.05       0  5011.3    0.05       0
Bank Sta=5007.3,5011.3
Exp/Cntr=0.3,0.1

Type RM Length L Ch R = 1,13652,470,470,470
BEGIN DESCRIPTION:
Mapping XS ba6e6071
END DESCRIPTION:
XS GIS Cut Line= 3
      1649972.34      6895819.21      1649890.69      6896247.18
      1650008.92      6896689.15
#Sta/Elev= 30
  4573.2 1836.43  4622.9 1834.70  4673.8 1833.52  4747.9 1833.07  4795.0 1831.73
  4800.1 1831.87  4826.5 1830.72  4852.2 1829.02  4857.3 1829.14  4877.4 1828.29
  4897.7 1826.79  4904.3 1825.94  4909.4 1826.14  4928.3 1824.38  4938.5 1823.89
  4956.5 1823.18  5018.1 1822.11  5018.3 1821.61  5021.8 1821.61  5022.1 1822.11
  5071.9 1822.71  5092.6 1824.41  5134.0 1825.96  5185.7 1826.88  5206.4 1827.71
  5247.8 1828.25  5258.2 1828.79  5320.6 1830.18  5361.7 1830.82  5466.4 1833.60
#Mann=3,-1,0
  4573.2    0.05       0  5018.1    0.05       0  5022.1    0.05       0
Bank Sta=5018.1,5022.1
Exp/Cntr=0.3,0.1

Type RM Length L Ch R = 1,13182,424,424,424
BEGIN DESCRIPTION:
Deadman 42 25.0
END DESCRIPTION:
XS GIS Cut Line= 3
      1649954.98      6895738.02      1649455.00      6896238.00
      1649355.00      6896738.01
#Sta/Elev= 30
  4288.5 1836.96  4302.6 1837.06  4316.8 1836.30  4330.9 1836.05  4373.3 1834.38
  4458.2 1832.17  4627.9 1830.37  4656.2 1829.81  4712.7 1828.38  4769.3 1826.21
  4811.7 1825.78  4882.4 1822.22  4967.3 1820.69  5003.7 1819.66  5004.0 1819.16
  5007.6 1819.16  5007.8 1819.66  5026.2 1819.80  5046.6 1820.69  5097.6 1821.17
  5128.2 1822.11  5189.3 1824.42  5270.9 1826.96  5281.1 1827.82  5301.5 1828.70
  5342.3 1829.67  5393.3 1831.42  5413.7 1832.31  5444.3 1834.33  5505.5 1835.71
#Mann=3,-1,0
  4288.5    0.05       0  5003.7    0.03       0  5007.8    0.05       0
Bank Sta=5003.7,5007.8
Exp/Cntr=0.3,0.1

Type RM Length L Ch R = 1,12758,468,468,468
BEGIN DESCRIPTION:
Deadman 42 24.0
END DESCRIPTION:
XS GIS Cut Line= 3
      1649255.01      6895637.98      1649105.00      6896188.00
      1648805.01      6896587.99
#Sta/Elev= 30
  4430.2 1833.98  4452.7 1833.02  4513.1 1832.12  4554.6 1829.84  4641.0 1826.86
  4658.3 1826.97  4730.8 1823.81  4761.9 1822.87  4869.0 1820.47  4896.7 1820.27
  4917.4 1819.23  4938.1 1819.43  4958.9 1818.63  4989.9 1818.84  5022.2 1817.52
  5034.7 1817.49  5035.0 1816.99  5038.6 1816.99  5038.9 1817.49  5072.2 1818.09
  5086.8 1819.79  5093.0 1819.46  5107.6 1820.38  5143.0 1821.02  5272.2 1825.98
  5286.8 1826.10  5363.9 1828.59  5400.3 1831.11  5422.2 1831.89  5500.3 1833.92
#Mann=3,-1,0
  4430.2    0.05       0  5034.7    0.05       0  5038.9    0.05       0
Bank Sta=5034.7,5038.9
Exp/Cntr=0.3,0.1

Type RM Length L Ch R = 1,12290,485,485,485
BEGIN DESCRIPTION:
Deadman 42 23.0
END DESCRIPTION:
XS GIS Cut Line= 3
      1648905.02      6895637.97      1648755.00      6895938.00
      1648705.00      6896437.96
#Sta/Elev= 30
  4668.8 1830.06  4699.6 1829.20  4721.9 1828.06  4727.5 1828.04  4766.7 1825.43
  4839.3 1822.63  4856.1 1821.40  4861.7 1821.36  4878.5 1819.92  4906.4 1818.70
  4923.2 1816.99  4951.1 1815.36  4967.9 1814.79  4993.8 1814.54  4994.0 1814.04
  4997.7 1814.04  4998.0 1814.54  5006.8 1814.82  5034.4 1816.80  5044.4 1817.21
  5057.0 1817.04  5074.6 1817.69  5104.7 1818.02  5295.7 1823.42  5335.9 1824.88
  5358.5 1826.48  5459.0 1829.18  5476.6 1829.98  5496.7 1831.44  5506.7 1831.72
#Mann=3,-1,0
  4668.8    0.05       0  4993.8    0.03       0  4998.0    0.05       0
Bank Sta=4993.8,4998
Exp/Cntr=0.3,0.1

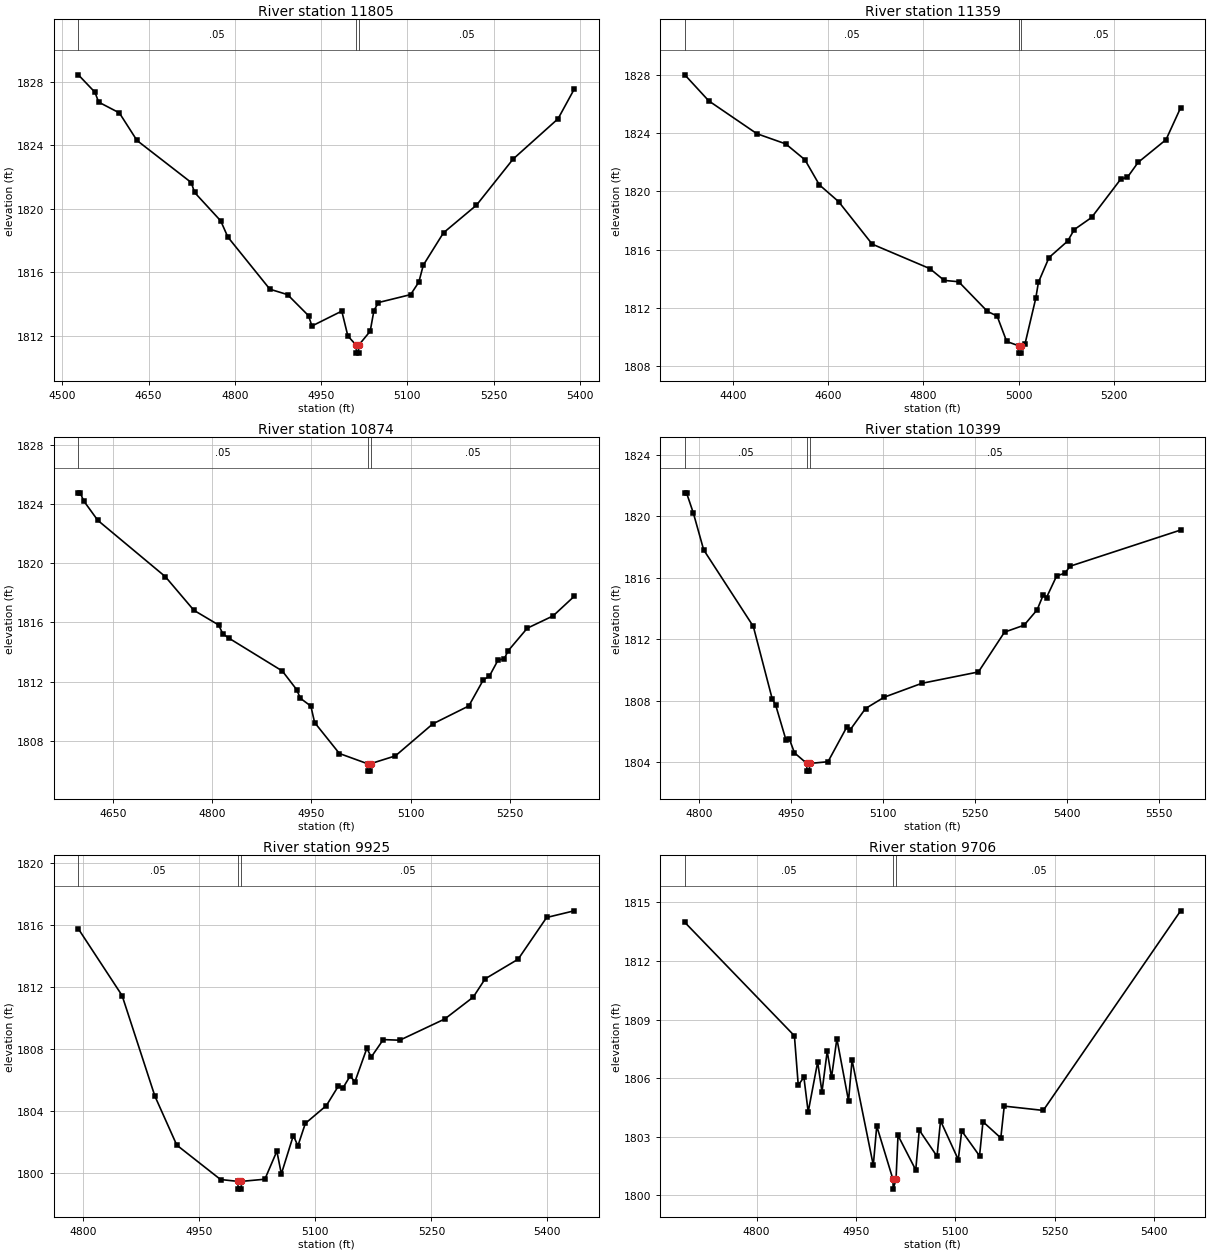
Type RM Length L Ch R = 1,11805,446,446,446
BEGIN DESCRIPTION:
Deadman 42 22.0
END DESCRIPTION:
XS GIS Cut Line= 3
      1648704.97      6895588.02      1648305.00      6895838.00
      1648054.98      6896138.02
#Sta/Elev= 30
  4527.8 1828.44  4556.7 1827.34  4563.1 1826.72  4599.1 1826.04  4629.8 1824.30
  4724.1 1821.65  4730.0 1821.02  4775.4 1819.23  4787.8 1818.21  4860.9 1814.92
  4891.6 1814.58  4928.1 1813.25  4934.0 1812.60  4985.9 1813.54  4996.5 1811.97
  5011.0 1811.39  5011.3 1810.89  5015.0 1810.89  5015.3 1811.39  5035.3 1812.27
  5041.8 1813.57  5049.6 1814.08  5105.6 1814.58  5119.9 1815.37  5127.7 1816.44
  5162.8 1818.48  5220.1 1820.22  5283.9 1823.13  5362.0 1825.67  5390.0 1827.53
#Mann=3,-1,0
  4527.8    0.05       0  5011.0    0.03       0  5015.3    0.05       0
Bank Sta=5011,5015.3
Exp/Cntr=0.3,0.1

Type RM Length L Ch R = 1,11359,485,485,485
BEGIN DESCRIPTION:
Deadman 42 21.0
END DESCRIPTION:
XS GIS Cut Line= 3
      1648655.03      6895488.00      1647955.00      6895588.00
      1647805.02      6895887.96
#Sta/Elev= 30
  4298.2 1827.99  4348.7 1826.20  4449.7 1823.95  4510.4 1823.25  4550.8 1822.16
  4581.1 1820.44  4621.5 1819.29  4692.2 1816.37  4813.4 1814.69  4843.7 1813.88
  4874.0 1813.79  4934.6 1811.75  4954.8 1811.44  4975.0 1809.69  5000.7 1809.39
  5001.0 1808.89  5004.7 1808.89  5005.0 1809.39  5013.7 1809.55  5036.1 1812.65
  5041.7 1813.75  5064.0 1815.45  5103.2 1816.58  5117.1 1817.37  5153.5 1818.20
  5215.0 1820.84  5228.9 1820.96  5251.3 1821.98  5310.0 1823.54  5340.7 1825.73
#Mann=3,-1,0
  4298.2    0.05       0  5000.7    0.05       0  5005.0    0.05       0
Bank Sta=5000.7,5005
Exp/Cntr=0.3,0.1

Type RM Length L Ch R = 1,10874,475,475,475
BEGIN DESCRIPTION:
Deadman 42 20.0
END DESCRIPTION:
XS GIS Cut Line= 3
      1648054.99      6894788.02      1647855.00      6895138.00
      1647706.57      6895452.21
#Sta/Elev= 30
  4597.1 1824.75  4600.0 1824.75  4605.0 1824.22  4626.6 1822.89  4728.8 1819.09
  4772.0 1816.82  4809.4 1815.83  4815.9 1815.23  4825.3 1814.93  4905.9 1812.72
  4927.5 1811.47  4933.2 1810.88  4949.1 1810.35  4954.8 1809.24  4992.3 1807.15
  5034.9 1806.46  5035.2 1805.96  5039.1 1805.96  5039.4 1806.46  5077.1 1806.99
  5133.7 1809.15  5188.2 1810.36  5210.3 1812.13  5219.2 1812.36  5232.4 1813.45
  5242.0 1813.55  5247.5 1814.07  5276.7 1815.61  5315.8 1816.44  5347.7 1817.76
#Mann=3,-1,0
  4597.1    0.05       0  5034.9    0.05       0  5039.4    0.05       0
Bank Sta=5034.9,5039.4
Exp/Cntr=0.3,0.1

Type RM Length L Ch R = 1,10399,474,474,474
BEGIN DESCRIPTION:
Deadman 42 19.0
END DESCRIPTION:
XS GIS Cut Line= 3
      1647354.99      6894737.98      1647455.00      6894938.00
      1647655.01      6895488.03
#Sta/Elev= 30
  4776.7 1821.53  4779.5 1821.53  4790.7 1820.21  4807.5 1817.82  4888.5 1812.84
  4919.3 1808.13  4924.9 1807.73  4941.6 1805.48  4947.2 1805.53  4955.6 1804.62
  4975.7 1803.93  4976.0 1803.43  4979.9 1803.43  4980.3 1803.93  5010.3 1804.04
  5040.9 1806.29  5046.2 1806.10  5071.5 1807.50  5102.1 1808.24  5163.3 1809.14
  5255.7 1809.88  5298.3 1812.47  5330.2 1812.92  5351.5 1813.92  5361.4 1814.88
  5366.8 1814.72  5383.4 1816.13  5397.4 1816.31  5404.7 1816.75  5585.6 1819.11
#Mann=3,-1,0
  4776.7    0.05       0  4975.7    0.05       0  4980.3    0.05       0
Bank Sta=4975.7,4980.3
Exp/Cntr=0.3,0.1

Type RM Length L Ch R = 1,9925,219,219,219
BEGIN DESCRIPTION:
Deadman 42 18.0
END DESCRIPTION:
XS GIS Cut Line= 3
      1647004.99      6895087.99      1647155.00      6895238.00
      1647521.54      6895460.81
#Sta/Elev= 30
  4793.5 1815.74  4850.1 1811.43  4892.5 1804.94  4920.8 1801.78  4977.4 1799.56
  4999.8 1799.44  5000.1 1798.94  5004.1 1798.94  5004.4 1799.44  5034.7 1799.58
  5050.2 1801.39  5056.0 1799.92  5071.5 1802.40  5077.4 1801.73  5087.0 1803.18
  5114.2 1804.33  5129.7 1805.59  5135.5 1805.46  5145.1 1806.25  5151.0 1805.85
  5166.5 1808.02  5172.3 1807.47  5187.8 1808.59  5209.1 1808.55  5267.3 1809.92
  5304.1 1811.33  5319.5 1812.51  5362.2 1813.78  5399.0 1816.47  5434.6 1816.90
#Mann=3,-1,0
  4793.5    0.05       0  4999.8    0.05       0  5004.4    0.05       0
Bank Sta=4999.8,5004.4
Exp/Cntr=0.3,0.1

Type RM Length L Ch R = 1,9706,71,71,71
BEGIN DESCRIPTION:
Mapping XS 0a0019e7
END DESCRIPTION:
XS GIS Cut Line= 4
      1646813.67      6895207.41      1646921.30      6895341.94
      1646957.81      6895386.15      1647451.85      6895545.08
#Sta/Elev= 30
  4691.6 1813.98  4857.1 1808.17  4862.9 1805.64  4871.4 1806.05  4877.9 1804.27
  4892.2 1806.83  4898.7 1805.30  4906.6 1807.38  4913.1 1806.04  4921.2 1808.02
  4938.8 1804.84  4944.1 1806.93  4976.2 1801.54  4981.4 1803.55  5005.9 1800.82
  5006.2 1800.32  5010.5 1800.82  5013.5 1803.07  5040.3 1801.30  5045.6 1803.34
  5072.4 1802.00  5077.7 1803.82  5104.5 1801.83  5109.7 1803.30  5136.6 1802.02
  5141.8 1803.77  5168.7 1802.94  5173.9 1804.57  5232.8 1804.35  5440.2 1814.57
#Mann=3,-1,0
  4691.6    0.05       0  5005.9    0.05       0  5010.5    0.05       0
Bank Sta=5005.9,5010.5
Exp/Cntr=0.3,0.1

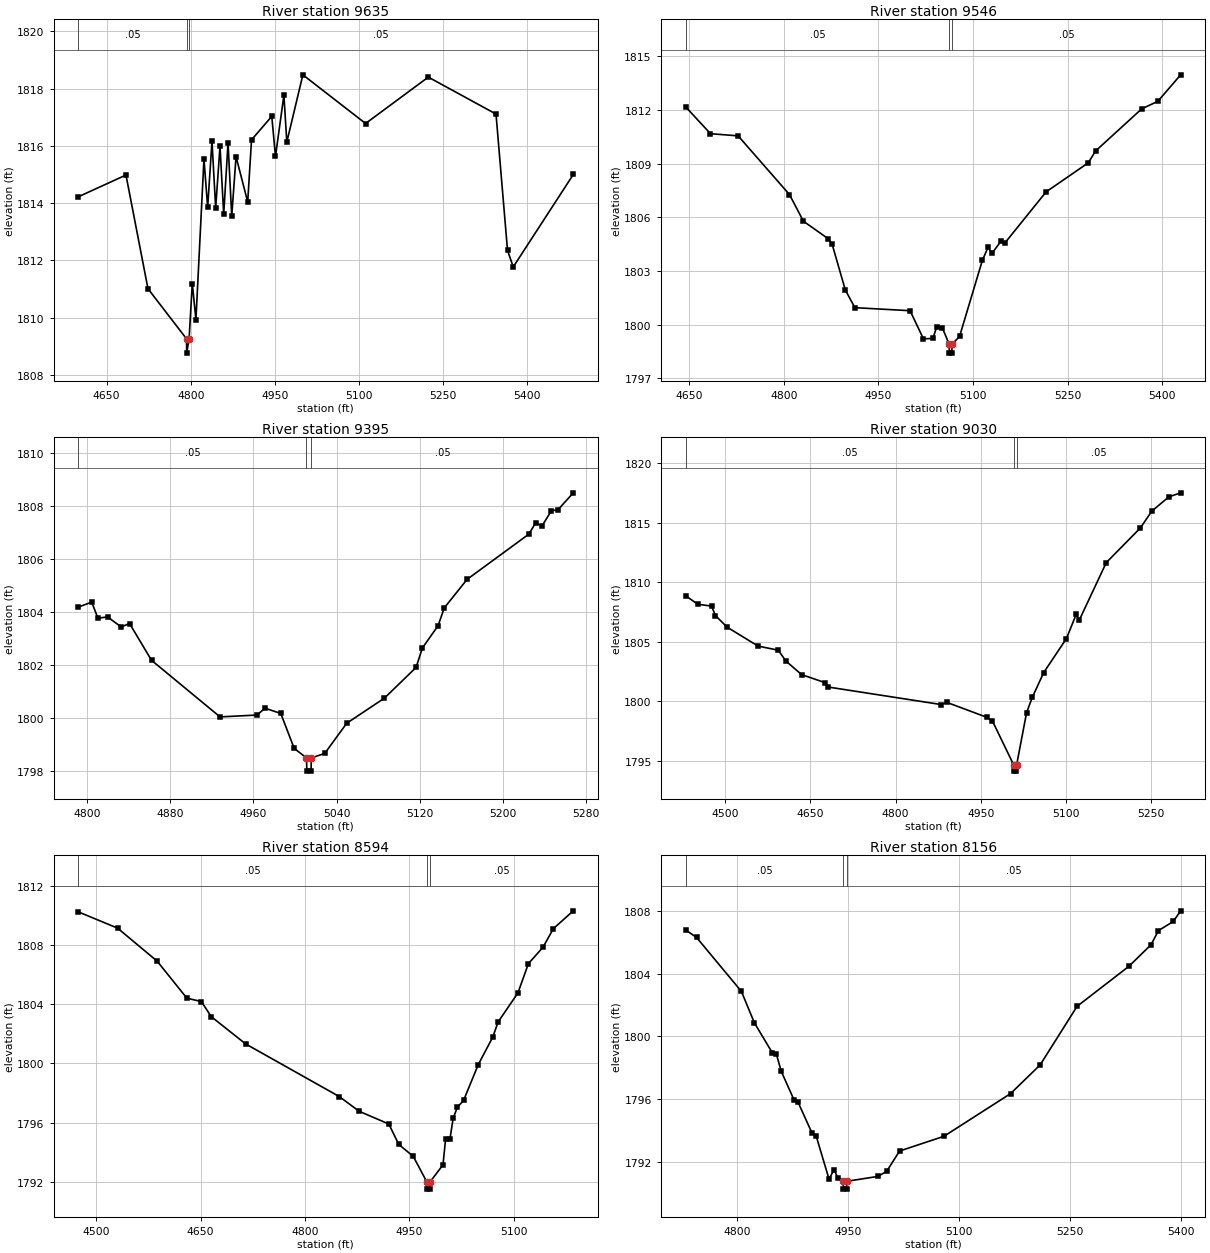
Type RM Length L Ch R = 1,9635,89,89,89
BEGIN DESCRIPTION:
Mapping XS b17c571c
END DESCRIPTION:
XS GIS Cut Line= 5
      1646785.40      6895166.11      1646838.89      6895354.73
      1646965.58      6895461.71      1647241.48      6895540.54
      1647469.50      6895591.21
#Sta/Elev= 30
  4599.5 1814.22  4684.5 1814.98  4723.7 1811.01  4792.4 1809.26  4792.7 1808.76
  4797.0 1809.26  4802.7 1811.19  4809.2 1809.93  4823.5 1815.54  4830.1 1813.85
  4837.8 1816.16  4844.4 1813.83  4852.1 1815.99  4858.7 1813.61  4866.4 1816.10
  4873.0 1813.55  4880.7 1815.62  4901.5 1814.04  4908.3 1816.21  4944.4 1817.03
  4951.0 1815.63  4966.0 1817.77  4971.2 1816.13  4999.8 1818.48  5111.6 1816.78
  5223.4 1818.40  5344.1 1817.11  5364.6 1812.35  5374.8 1811.77  5481.9 1815.00
#Mann=3,-1,0
  4599.5    0.05       0  4792.4    0.05       0  4797.0    0.05       0
Bank Sta=4792.4,4797
Exp/Cntr=0.3,0.1

Type RM Length L Ch R = 1,9546,151,151,151
BEGIN DESCRIPTION:
Mapping XS 9d5cd861
END DESCRIPTION:
XS GIS Cut Line= 4
      1646757.24      6895270.24      1646810.73      6895450.45
      1647078.19      6895625.00      1647344.22      6895703.41
#Sta/Elev= 30
  4644.3 1812.17  4683.7 1810.67  4727.5 1810.55  4808.9 1807.27  4831.0 1805.78
  4870.4 1804.80  4876.4 1804.51  4897.4 1801.94  4912.6 1800.95  5000.1 1800.78
  5021.2 1799.21  5036.3 1799.23  5042.3 1799.88  5051.4 1799.81  5062.0 1798.91
  5062.3 1798.41  5066.3 1798.41  5066.6 1798.91  5078.5 1799.34  5114.7 1803.60
  5123.8 1804.33  5129.8 1803.98  5144.9 1804.70  5149.8 1804.54  5215.7 1807.42
  5282.4 1809.04  5294.3 1809.71  5367.3 1812.06  5392.8 1812.48  5429.0 1813.96
#Mann=3,-1,0
  4644.3    0.05       0  5062.0    0.03       0  5066.6    0.05       0
Bank Sta=5062,5066.6
Exp/Cntr=0.3,0.1

Type RM Length L Ch R = 1,9395,365,365,365
BEGIN DESCRIPTION:
Mapping XS 93bf9b90
END DESCRIPTION:
XS GIS Cut Line= 2
      1646700.27      6895555.27      1647100.98      6895812.19
#Sta/Elev= 30
  4791.7 1804.19  4804.6 1804.38  4810.6 1803.77  4819.8 1803.82  4833.0 1803.44
  4841.0 1803.57  4862.1 1802.18  4928.0 1800.04  4963.6 1800.11  4971.2 1800.37
  4986.4 1800.17  4999.3 1798.85  5011.1 1798.49  5011.5 1797.99  5015.5 1797.99
  5015.8 1798.49  5028.7 1798.66  5049.8 1799.80  5086.1 1800.75  5116.5 1801.91
  5122.5 1802.64  5137.7 1803.49  5143.6 1804.16  5165.6 1805.24  5225.0 1806.95
  5231.5 1807.38  5237.5 1807.25  5246.7 1807.84  5252.7 1807.86  5267.7 1808.51
#Mann=3,-1,0
  4791.7    0.05       0  5011.1    0.03       0  5015.8    0.05       0
Bank Sta=5011.1,5015.8
Exp/Cntr=0.3,0.1

Type RM Length L Ch R = 1,9030,436,436,436
BEGIN DESCRIPTION:
Mapping XS 0cdfb06b
END DESCRIPTION:
XS GIS Cut Line= 3
      1646700.93      6895377.28      1646630.55      6895653.15
      1646658.71      6896238.77
#Sta/Elev= 30
  4430.7 1808.87  4452.1 1808.16  4476.4 1808.00  4483.0 1807.21  4503.7 1806.23
  4558.1 1804.64  4593.8 1804.29  4606.9 1803.39  4634.7 1802.24  4675.6 1801.57
  4680.7 1801.20  4880.4 1799.72  4890.5 1799.90  4960.5 1798.65  4970.6 1798.33
  5008.1 1794.62  5008.5 1794.12  5012.7 1794.12  5013.0 1794.62  5030.6 1799.04
  5040.6 1800.32  5060.7 1802.41  5100.7 1805.27  5118.0 1807.32  5123.1 1806.80
  5170.8 1811.66  5230.9 1814.58  5250.9 1815.99  5280.9 1817.19  5301.7 1817.53
#Mann=3,-1,0
  4430.7    0.05       0  5008.1    0.03       0  5013.0    0.05       0
Bank Sta=5008.1,5013
Exp/Cntr=0.3,0.1

Type RM Length L Ch R = 1,8594,438,438,438
BEGIN DESCRIPTION:
Deadman 42 15.0
END DESCRIPTION:
XS GIS Cut Line= 3
      1646654.99      6895288.01      1646305.00      6895688.00
      1646204.98      6895838.02
#Sta/Elev= 30
  4474.2 1810.23  4530.7 1809.13  4587.6 1806.90  4630.3 1804.40  4651.2 1804.17
  4665.4 1803.15  4714.8 1801.31  4849.6 1797.75  4878.0 1796.76  4920.7 1795.90
  4935.0 1794.52  4955.9 1793.71  4975.2 1792.00  4975.6 1791.50  4979.8 1791.50
  4980.2 1792.00  4998.6 1793.14  5002.4 1794.91  5008.7 1794.91  5013.2 1796.28
  5019.2 1797.03  5028.2 1797.49  5049.3 1799.91  5070.3 1801.78  5077.8 1802.79
  5106.3 1804.75  5121.4 1806.73  5142.4 1807.84  5157.4 1809.10  5186.0 1810.30
#Mann=3,-1,0
  4474.2    0.05       0  4975.2    0.05       0  4980.2    0.05       0
Bank Sta=4975.2,4980.2
Exp/Cntr=0.3,0.1

Type RM Length L Ch R = 1,8156,471,471,471
BEGIN DESCRIPTION:
Deadman 42 14.0
END DESCRIPTION:
XS GIS Cut Line= 3
      1646105.00      6895138.01      1646005.00      6895388.00
      1646005.00      6895787.96
#Sta/Elev= 30
  4730.6 1806.79  4745.4 1806.31  4806.0 1802.87  4823.5 1800.87  4847.7 1798.96
  4853.1 1798.90  4859.8 1797.78  4877.3 1795.93  4882.7 1795.79  4901.6 1793.82
  4907.0 1793.66  4924.5 1790.89  4931.2 1791.51  4936.6 1790.94  4943.5 1790.76
  4943.9 1790.26  4948.1 1790.26  4948.5 1790.76  4990.4 1791.07  5002.3 1791.39
  5019.8 1792.69  5079.8 1793.63  5169.8 1796.35  5209.8 1798.18  5259.8 1801.92
  5329.8 1804.47  5359.8 1805.85  5369.8 1806.75  5389.8 1807.33  5399.8 1808.01
#Mann=3,-1,0
  4730.6    0.05       0  4943.5    0.03       0  4948.5    0.05       0
Bank Sta=4943.5,4948.5
Exp/Cntr=0.3,0.1

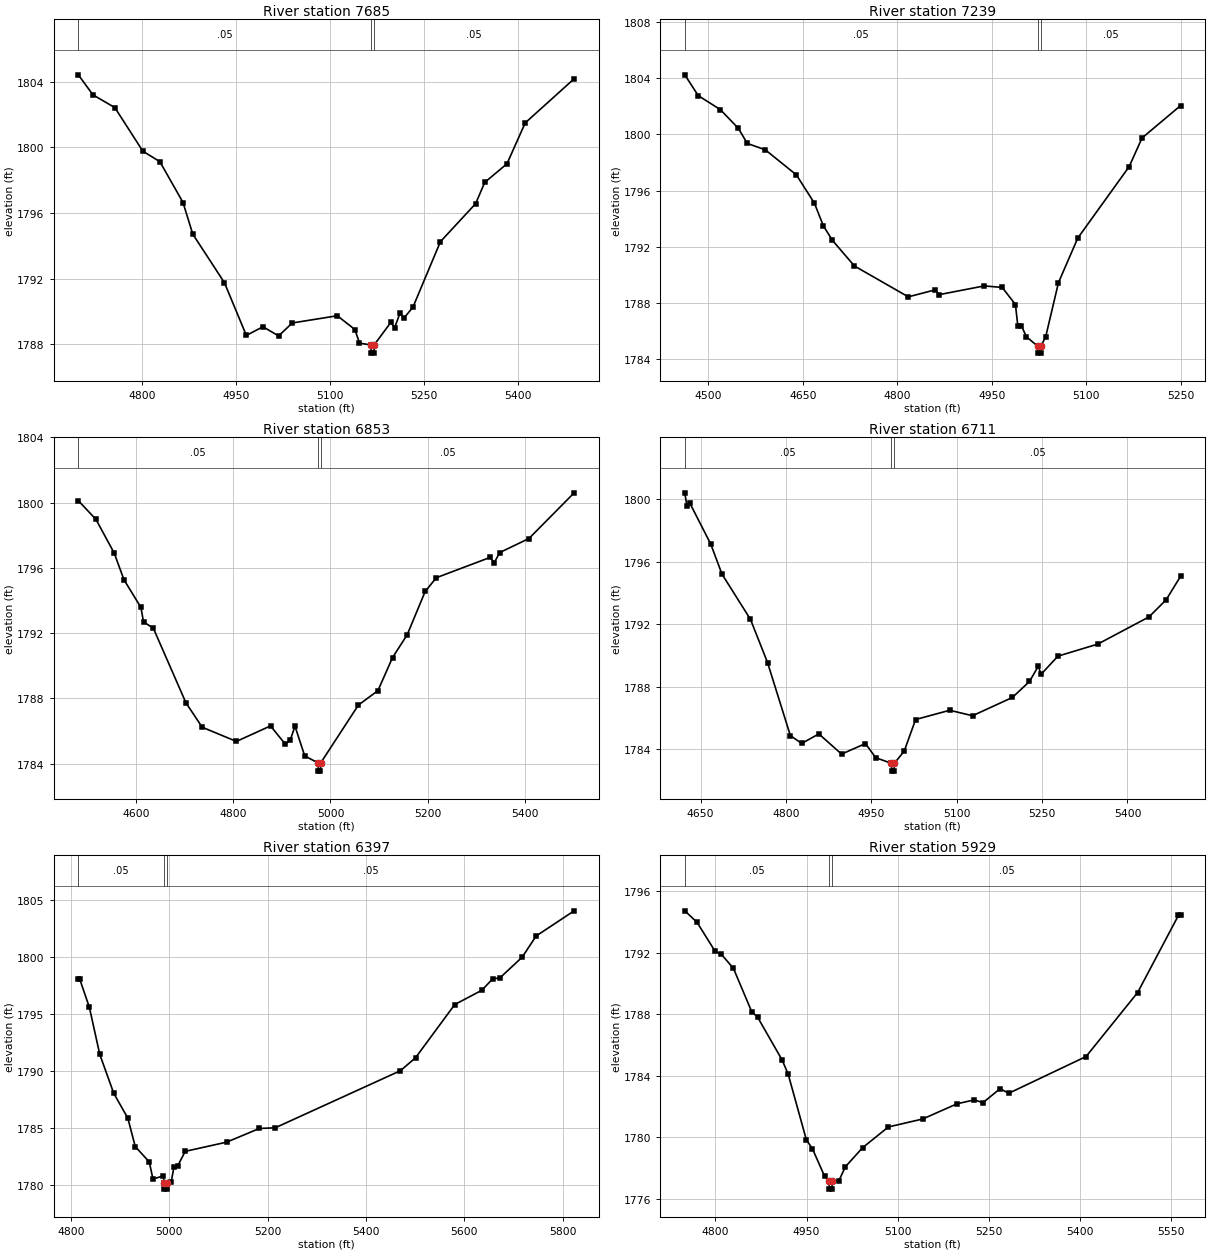
Type RM Length L Ch R = 1,7685,446,446,446
BEGIN DESCRIPTION:
Deadman 42 13.0
END DESCRIPTION:
XS GIS Cut Line= 3
      1645754.99      6894988.01      1645605.00      6895238.00
      1645305.02      6895637.98
#Sta/Elev= 30
  4698.5 1804.43  4721.8 1803.21  4756.8 1802.43  4801.5 1799.77  4828.7 1799.13
  4865.6 1796.64  4881.2 1794.71  4931.7 1791.75  4966.7 1788.53  4993.2 1789.06
  5018.2 1788.50  5040.0 1789.29  5111.9 1789.73  5140.0 1788.89  5147.3 1788.06
  5165.6 1787.95  5166.0 1787.45  5170.4 1787.45  5170.7 1787.95  5197.3 1789.32
  5203.6 1789.01  5211.9 1789.89  5218.2 1789.58  5232.7 1790.26  5276.5 1794.25
  5332.7 1796.57  5347.3 1797.87  5382.7 1799.00  5411.9 1801.50  5490.0 1804.19
#Mann=3,-1,0
  4698.5    0.05       0  5165.6    0.03       0  5170.7    0.05       0
Bank Sta=5165.6,5170.7
Exp/Cntr=0.3,0.1

Type RM Length L Ch R = 1,7239,386,386,386
BEGIN DESCRIPTION:
Deadman 42 12.0
END DESCRIPTION:
XS GIS Cut Line= 3
      1645604.98      6894888.02      1645255.00      6895288.00
      1645205.01      6895537.97
#Sta/Elev= 30
  4463.0 1804.25  4484.3 1802.77  4519.4 1801.77  4547.9 1800.44  4562.2 1799.36
  4590.6 1798.91  4640.0 1797.12  4668.5 1795.11  4682.7 1793.50  4696.9 1792.47
  4732.0 1790.63  4817.5 1788.43  4860.2 1788.93  4866.8 1788.59  4938.0 1789.21
  4966.5 1789.10  4987.4 1787.88  4991.2 1786.36  4997.0 1786.36  5004.7 1785.59
  5022.5 1784.92  5022.9 1784.42  5027.3 1784.42  5027.7 1784.92  5035.3 1785.57
  5055.7 1789.45  5086.3 1792.62  5167.8 1797.71  5188.2 1799.75  5249.4 1802.06
#Mann=3,-1,0
  4463.0    0.05       0  5022.5    0.05       0  5027.7    0.05       0
Bank Sta=5022.5,5027.7
Exp/Cntr=0.3,0.1

Type RM Length L Ch R = 1,6853,142,142,142
BEGIN DESCRIPTION:
Deadman 42 11.0
END DESCRIPTION:
XS GIS Cut Line= 3
      1644983.59      6894594.57      1644927.29      6895123.87
      1644961.07      6895610.92
#Sta/Elev= 30
  4481.0 1800.12  4517.3 1798.97  4554.8 1796.91  4575.0 1795.27  4609.8 1793.58
  4615.2 1792.69  4635.3 1792.31  4702.4 1787.74  4735.9 1786.24  4806.3 1785.37
  4876.6 1786.32  4906.8 1785.21  4916.9 1785.43  4926.9 1786.30  4947.0 1784.48
  4974.6 1784.05  4975.0 1783.55  4979.4 1783.55  4979.8 1784.05  5057.5 1787.60
  5097.6 1788.48  5127.7 1790.51  5157.8 1791.90  5194.9 1794.56  5217.9 1795.40
  5328.2 1796.64  5337.3 1796.33  5348.2 1796.94  5408.4 1797.80  5501.5 1800.60
#Mann=3,-1,0
  4481.0    0.05       0  4974.6    0.05       0  4979.8    0.05       0
Bank Sta=4974.6,4979.8
Exp/Cntr=0.3,0.1

Type RM Length L Ch R = 1,6711,314,314,314
BEGIN DESCRIPTION:
Mapping XS 22e6e2bb
END DESCRIPTION:
XS GIS Cut Line= 2
      1644840.23      6894632.64      1644811.87      6895503.48
#Sta/Elev= 30
  4622.1 1800.40  4625.8 1799.57  4630.8 1799.75  4667.5 1797.14  4687.5 1795.20
  4737.5 1792.31  4767.5 1789.55  4807.6 1784.88  4827.6 1784.38  4857.6 1784.99
  4897.6 1783.70  4939.5 1784.37  4957.6 1783.47  4985.1 1783.11  4985.5 1782.61
  4989.9 1782.61  4990.3 1783.11  5007.7 1783.89  5027.7 1785.91  5087.7 1786.50
  5127.7 1786.15  5197.8 1787.32  5227.8 1788.34  5243.2 1789.31  5248.2 1788.80
  5277.8 1789.96  5347.8 1790.73  5437.9 1792.47  5467.9 1793.56  5493.4 1795.07
#Mann=3,-1,0
  4622.1    0.05       0  4985.1    0.03       0  4990.3    0.05       0
Bank Sta=4985.1,4990.3
Exp/Cntr=0.3,0.1

Type RM Length L Ch R = 1,6397,468,468,468
BEGIN DESCRIPTION:
Deadman 42 10.0
END DESCRIPTION:
XS GIS Cut Line= 3
      1644455.01      6894838.02      1644555.00      6894988.00
      1644905.00      6895738.00
#Sta/Elev= 30
  4815.2 1798.04  4818.2 1798.04  4837.7 1795.57  4858.7 1791.45  4887.3 1788.01
  4915.8 1785.84  4930.9 1783.34  4959.4 1781.99  4966.9 1780.49  4987.9 1780.76
  4989.8 1780.10  4990.3 1779.60  4994.7 1779.60  4995.1 1780.10  5004.1 1780.27
  5009.6 1781.54  5017.5 1781.67  5032.5 1782.92  5116.8 1783.73  5183.1 1784.93
  5215.4 1784.99  5470.0 1790.01  5500.7 1791.15  5580.3 1795.82  5635.5 1797.08
  5657.6 1798.09  5671.8 1798.15  5717.5 1799.99  5745.9 1801.85  5823.1 1804.06
#Mann=3,-1,0
  4815.2    0.05       0  4989.8    0.05       0  4995.1    0.05       0
Bank Sta=4989.8,4995.1
Exp/Cntr=0.3,0.1

Type RM Length L Ch R = 1,5929,468,468,468
BEGIN DESCRIPTION:
Deadman 42 9.0
END DESCRIPTION:
XS GIS Cut Line= 3
      1644205.00      6895038.04      1644205.00      6895288.00
      1644604.96      6895687.96
#Sta/Elev= 30
  4749.7 1794.71  4769.7 1793.97  4799.7 1792.07  4809.7 1791.89  4829.7 1790.97
  4859.7 1788.16  4869.7 1787.78  4909.7 1785.02  4919.7 1784.10  4949.7 1779.82
  4959.7 1779.24  4979.7 1777.45  4987.0 1777.12  4987.4 1776.62  4991.9 1776.62
  4992.3 1777.12  5003.2 1777.17  5013.8 1778.07  5042.1 1779.31  5084.5 1780.66
  5141.1 1781.18  5197.7 1782.17  5225.9 1782.42  5240.1 1782.24  5268.4 1783.15
  5282.5 1782.85  5409.8 1785.24  5494.6 1789.40  5561.8 1794.42  5565.3 1794.42
#Mann=3,-1,0
  4749.7    0.05       0  4987.0    0.05       0  4992.3    0.05       0
Bank Sta=4987,4992.3
Exp/Cntr=0.3,0.1

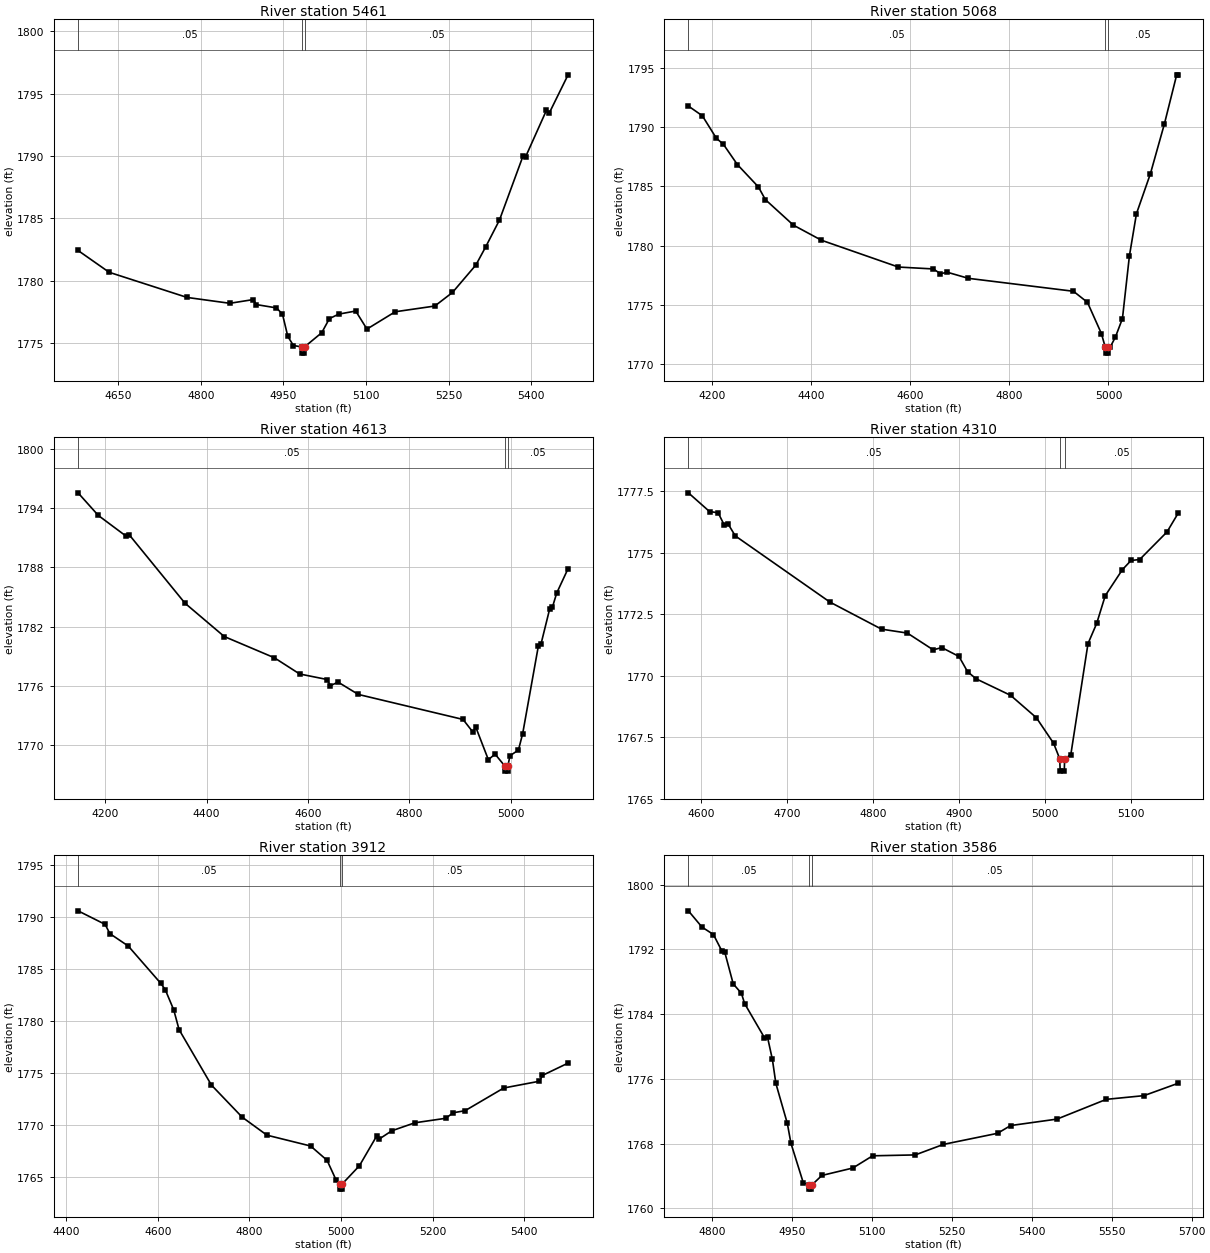
Type RM Length L Ch R = 1,5461,393,393,393
BEGIN DESCRIPTION:
Mapping XS a2eb8272
END DESCRIPTION:
XS GIS Cut Line= 3
      1644034.81      6895247.77      1643840.58      6895450.45
      1643978.35      6896043.74
#Sta/Elev= 30
  4577.3 1782.42  4633.8 1780.67  4775.3 1778.65  4852.9 1778.18  4895.6 1778.48
  4900.7 1778.08  4937.6 1777.81  4948.5 1777.31  4958.2 1775.52  4968.4 1774.79
  4983.3 1774.68  4983.7 1774.18  4988.2 1774.18  4988.6 1774.68  5019.8 1775.82
  5033.7 1776.95  5050.6 1777.31  5081.5 1777.56  5101.9 1776.11  5153.2 1777.50
  5225.1 1777.96  5257.2 1779.05  5299.8 1781.26  5317.5 1782.71  5342.5 1784.86
  5385.1 1789.98  5390.2 1789.96  5427.7 1793.66  5432.9 1793.45  5467.1 1796.52
#Mann=3,-1,0
  4577.3    0.05       0  4983.3    0.03       0  4988.6    0.05       0
Bank Sta=4983.3,4988.6
Exp/Cntr=0.3,0.1

Type RM Length L Ch R = 1,5068,455,455,455
BEGIN DESCRIPTION:
Deadman 42 8.0
END DESCRIPTION:
XS GIS Cut Line= 3
      1644154.97      6895088.03      1643555.00      6895688.00
      1643455.01      6895787.99
#Sta/Elev= 30
  4151.4 1791.76  4179.6 1790.94  4207.9 1789.05  4222.1 1788.54  4250.4 1786.83
  4292.8 1784.95  4306.9 1783.88  4363.5 1781.73  4420.1 1780.46  4575.6 1778.20
  4646.3 1778.04  4660.5 1777.64  4674.6 1777.76  4717.0 1777.25  4929.2 1776.16
  4957.5 1775.23  4985.7 1772.60  4993.5 1771.45  4994.0 1770.95  4998.7 1770.95
  4999.2 1771.45  5003.4 1771.45  5014.0 1772.30  5028.2 1773.86  5042.3 1779.14
  5056.5 1782.69  5084.7 1786.06  5113.0 1790.26  5137.8 1794.39  5141.3 1794.39
#Mann=3,-1,0
  4151.4    0.05       0  4993.5    0.05       0  4999.2    0.05       0
Bank Sta=4993.5,4999.2
Exp/Cntr=0.3,0.1

Type RM Length L Ch R = 1,4613,303,303,303
BEGIN DESCRIPTION:
Deadman 42 7.0
END DESCRIPTION:
XS GIS Cut Line= 3
      1644204.96      6894988.02      1643405.00      6895288.00
      1643304.96      6895338.02
#Sta/Elev= 30
  4146.5 1795.55  4186.5 1793.26  4241.7 1791.15  4247.0 1791.33  4357.4 1784.38
  4434.8 1781.01  4533.6 1778.86  4583.4 1777.22  4637.7 1776.66  4644.0 1776.03
  4659.1 1776.40  4699.1 1775.15  4905.6 1772.62  4925.2 1771.33  4930.5 1771.87
  4955.5 1768.55  4968.8 1769.11  4988.2 1767.89  4988.7 1767.39  4993.5 1767.39
  4993.9 1767.89  4998.2 1768.95  5014.8 1769.52  5023.2 1771.19  5054.0 1780.02
  5059.5 1780.29  5076.3 1783.78  5081.9 1783.99  5090.3 1785.41  5112.7 1787.88
#Mann=3,-1,0
  4146.5    0.05       0  4988.2    0.05       0  4993.9    0.05       0
Bank Sta=4988.2,4993.9
Exp/Cntr=0.3,0.1

Type RM Length L Ch R = 1,4310,398,398,398
BEGIN DESCRIPTION:
Mapping XS 24028ddc
END DESCRIPTION:
XS GIS Cut Line= 2
      1643819.54      6894960.46      1643249.93      6894993.96
#Sta/Elev= 30
  4584.9 1777.44  4609.5 1776.68  4619.5 1776.63  4626.4 1776.15  4631.4 1776.16
  4639.5 1775.69  4749.7 1773.00  4809.8 1771.90  4839.9 1771.74  4869.9 1771.06
  4880.0 1771.15  4900.0 1770.79  4910.0 1770.17  4920.0 1769.88  4960.1 1769.21
  4990.1 1768.30  5010.2 1767.26  5017.3 1766.63  5017.8 1766.13  5022.6 1766.13
  5023.0 1766.63  5030.2 1766.80  5050.2 1771.31  5060.3 1772.13  5070.3 1773.26
  5090.3 1774.32  5100.3 1774.69  5110.4 1774.73  5142.2 1775.85  5155.5 1776.63
#Mann=3,-1,0
  4584.9    0.05       0  5017.3    0.03       0  5023.0    0.05       0
Bank Sta=5017.3,5023
Exp/Cntr=0.3,0.1

Type RM Length L Ch R = 1,3912,326,326,326
BEGIN DESCRIPTION:
Mapping XS 8dc0318e
END DESCRIPTION:
XS GIS Cut Line= 3
      1644023.55      6894524.21      1643283.14      6894625.56
      1643179.48      6894930.93
#Sta/Elev= 30
  4425.9 1790.59  4485.0 1789.29  4495.4 1788.40  4535.5 1787.21  4606.1 1783.65
  4616.2 1783.03  4634.8 1781.08  4646.5 1779.18  4717.1 1773.86  4784.2 1770.78
  4838.3 1769.05  4933.6 1768.01  4969.5 1766.64  4989.7 1764.70  4996.9 1764.37
  4997.4 1763.87  5002.2 1763.87  5002.7 1764.37  5040.1 1766.11  5078.0 1768.98
  5083.1 1768.67  5110.8 1769.47  5161.2 1770.24  5228.6 1770.67  5244.8 1771.20
  5270.8 1771.40  5355.3 1773.58  5433.2 1774.23  5439.8 1774.79  5495.7 1775.97
#Mann=3,-1,0
  4425.9    0.05       0  4996.9    0.03       0  5002.7    0.05       0
Bank Sta=4996.9,5002.7
Exp/Cntr=0.3,0.1

Type RM Length L Ch R = 1,3586,390,390,390
BEGIN DESCRIPTION:
Mapping XS 2e035289
END DESCRIPTION:
XS GIS Cut Line= 3
      1643533.68      6894082.24      1643226.84      6894603.04
      1643156.46      6894909.90
#Sta/Elev= 30
  4755.9 1796.78  4781.4 1794.77  4802.9 1793.85  4818.5 1791.84  4824.3 1791.63
  4840.0 1787.75  4855.4 1786.58  4861.4 1785.31  4898.6 1781.09  4904.4 1781.14
  4913.5 1778.40  4920.0 1775.44  4941.5 1770.50  4948.3 1768.04  4971.5 1763.15
  4981.5 1762.87  4982.0 1762.37  4986.8 1762.37  4987.3 1762.87  5006.3 1764.06
  5064.4 1764.98  5101.5 1766.49  5181.5 1766.60  5234.3 1767.90  5335.8 1769.27
  5360.4 1770.23  5447.5 1771.03  5539.9 1773.47  5610.6 1773.93  5675.2 1775.47
#Mann=3,-1,0
  4755.9    0.05       0  4981.5    0.03       0  4987.3    0.05       0
Bank Sta=4981.5,4987.3
Exp/Cntr=0.3,0.1