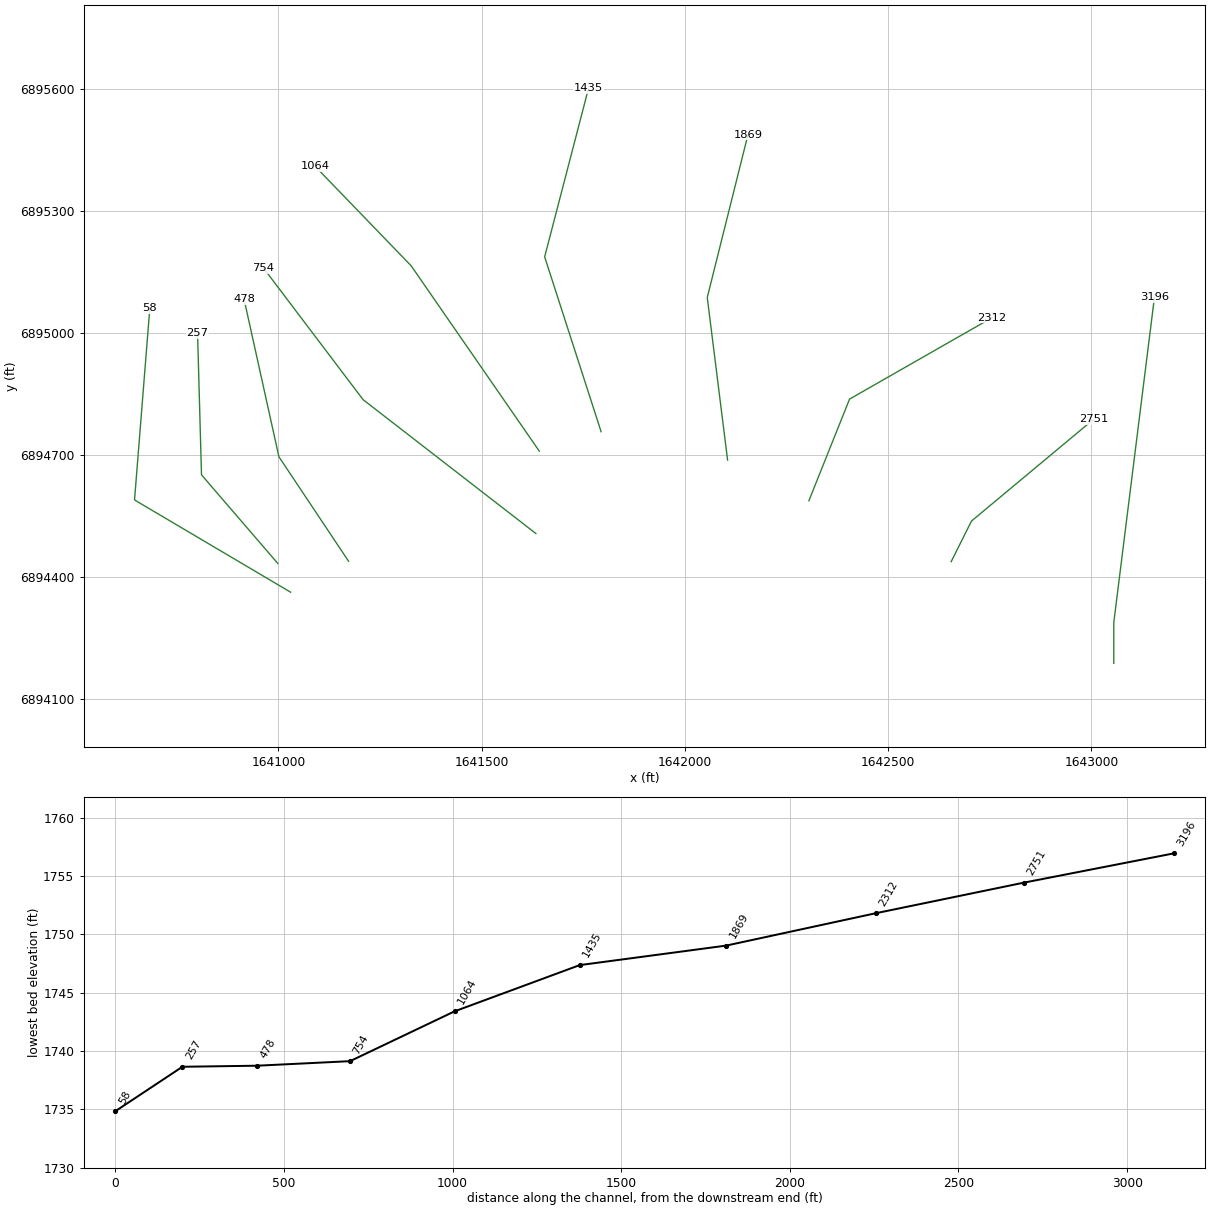
HEC-RAS study Deadman 42.prj: Deadman 42 Base Level Engineering

--- Deadman 42.g01 (geometry) --- (continued)

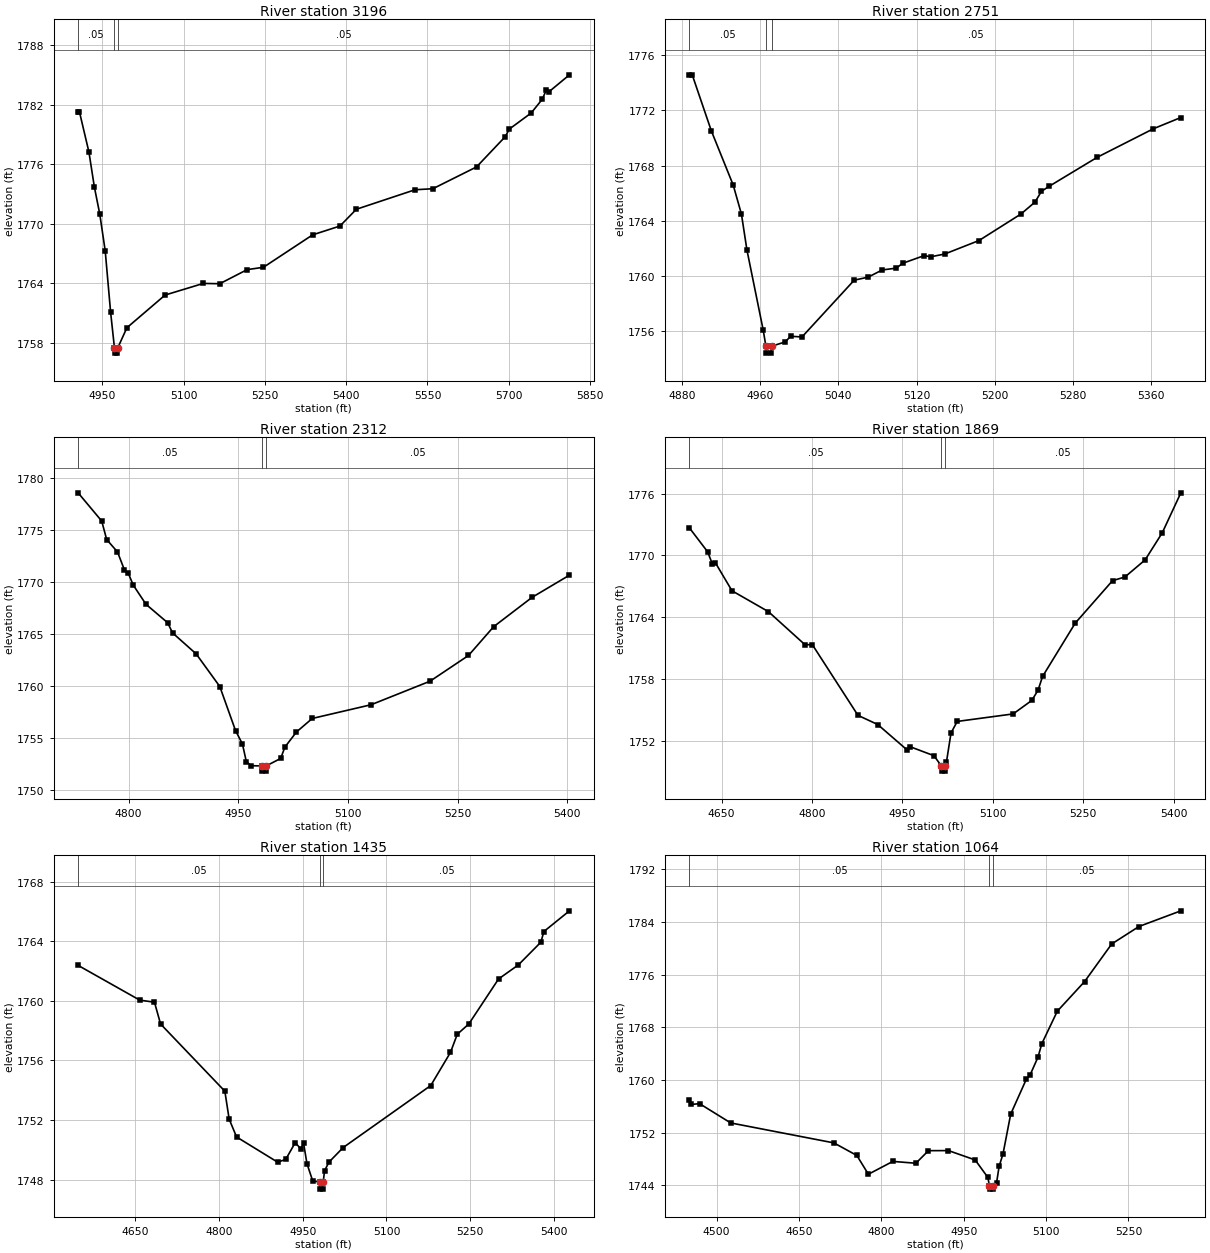
Type RM Length L Ch R = 1,3196,445,445,445
BEGIN DESCRIPTION:
Deadman 42 6.0
END DESCRIPTION:
XS GIS Cut Line= 3
      1643055.00      6894187.97      1643055.00      6894288.00
      1643155.01      6895088.04
#Sta/Elev= 30
  4905.6 1781.27  4908.1 1781.27  4925.6 1777.21  4935.6 1773.69  4945.6 1770.95
  4955.6 1767.25  4965.6 1761.04  4972.7 1757.44  4973.2 1756.94  4978.1 1756.94
  4978.5 1757.44  4995.6 1759.50  5066.1 1762.80  5136.6 1763.97  5166.9 1763.94
  5217.3 1765.36  5247.5 1765.60  5338.2 1768.87  5388.6 1769.76  5418.8 1771.45
  5527.2 1773.42  5559.9 1773.52  5640.5 1775.72  5693.4 1778.77  5701.0 1779.54
  5741.3 1781.16  5761.5 1782.53  5769.0 1783.44  5774.1 1783.30  5811.9 1785.01
#Mann=3,-1,0
  4905.6    0.05       0  4972.7    0.05       0  4978.5    0.05       0
Bank Sta=4972.7,4978.5
Exp/Cntr=0.3,0.1

Type RM Length L Ch R = 1,2751,439,439,439
BEGIN DESCRIPTION:
Deadman 42 5.0
END DESCRIPTION:
XS GIS Cut Line= 3
      1642655.01      6894438.02      1642705.00      6894538.00
      1643005.01      6894788.01
#Sta/Elev= 30
  4887.9 1774.57  4890.7 1774.57  4910.2 1770.52  4932.6 1766.59  4941.0 1764.49
  4946.6 1761.90  4963.3 1756.08  4966.0 1754.93  4966.5 1754.43  4971.4 1754.43
  4971.8 1754.93  4985.7 1755.24  4991.3 1755.65  5002.9 1755.60  5056.3 1759.71
  5070.6 1759.93  5084.9 1760.45  5099.3 1760.58  5105.8 1760.93  5127.9 1761.49
  5134.4 1761.40  5148.7 1761.60  5183.9 1762.58  5226.8 1764.50  5241.1 1765.36
  5247.7 1766.14  5255.5 1766.50  5304.9 1768.61  5362.2 1770.67  5390.2 1771.48
#Mann=3,-1,0
  4887.9    0.05       0  4966.0    0.05       0  4971.8    0.05       0
Bank Sta=4966,4971.8
Exp/Cntr=0.3,0.1

Type RM Length L Ch R = 1,2312,443,443,443
BEGIN DESCRIPTION:
Deadman 42 4.0
END DESCRIPTION:
XS GIS Cut Line= 3
      1642304.99      6894587.98      1642405.00      6894838.00
      1642755.00      6895038.00
#Sta/Elev= 30
  4730.8 1778.55  4763.1 1775.84  4769.9 1774.06  4784.7 1772.87  4794.1 1771.16
  4799.5 1770.82  4806.2 1769.69  4823.7 1767.84  4853.3 1766.07  4860.1 1765.09
  4892.4 1763.07  4924.7 1759.94  4946.2 1755.71  4955.7 1754.41  4961.0 1752.72
  4967.8 1752.33  4982.3 1752.31  4982.8 1751.81  4987.7 1751.81  4988.2 1752.31
  5008.0 1753.03  5013.8 1754.12  5029.6 1755.57  5051.2 1756.87  5131.8 1758.19
  5212.4 1760.45  5265.0 1762.92  5299.5 1765.69  5352.1 1768.51  5403.2 1770.64
#Mann=3,-1,0
  4730.8    0.05       0  4982.3    0.05       0  4988.2    0.05       0
Bank Sta=4982.3,4988.2
Exp/Cntr=0.3,0.1

Type RM Length L Ch R = 1,1869,434,434,434
BEGIN DESCRIPTION:
Deadman 42 3.0
END DESCRIPTION:
XS GIS Cut Line= 3
      1642105.00      6894688.03      1642055.00      6895088.00
      1642155.00      6895488.01
#Sta/Elev= 30
  4596.7 1772.67  4626.9 1770.35  4634.5 1769.19  4639.5 1769.31  4667.2 1766.57
  4727.7 1764.54  4788.1 1761.34  4800.7 1761.32  4876.3 1754.46  4909.1 1753.57
  4957.0 1751.14  4962.0 1751.43  5002.4 1750.54  5014.7 1749.54  5015.2 1749.04
  5020.4 1749.04  5020.9 1749.54  5023.0 1749.88  5030.7 1752.75  5041.0 1753.87
  5133.8 1754.60  5164.7 1755.91  5175.0 1756.89  5182.7 1758.25  5236.9 1763.43
  5298.7 1767.55  5319.3 1767.91  5352.8 1769.57  5381.2 1772.20  5412.1 1776.09
#Mann=3,-1,0
  4596.7    0.05       0  5014.7    0.05       0  5020.9    0.05       0
Bank Sta=5014.7,5020.9
Exp/Cntr=0.3,0.1

Type RM Length L Ch R = 1,1435,371,371,371
BEGIN DESCRIPTION:
Deadman 42 2.0
END DESCRIPTION:
XS GIS Cut Line= 3
      1641793.85      6894757.84      1641655.00      6895188.00
      1641762.87      6895602.47
#Sta/Elev= 30
  4547.5 1762.38  4657.9 1760.05  4684.3 1759.91  4695.2 1758.45  4810.4 1753.94
  4818.1 1752.07  4831.4 1750.87  4904.9 1749.18  4919.4 1749.36  4936.5 1750.49
  4946.2 1750.08  4951.5 1750.44  4957.5 1749.08  4968.0 1747.90  4980.3 1747.87
  4980.8 1747.37  4986.2 1747.37  4986.7 1747.87  4989.0 1748.60  4996.9 1749.18
  5022.4 1750.16  5179.3 1754.32  5214.6 1756.54  5226.8 1757.76  5247.5 1758.45
  5300.8 1761.47  5336.2 1762.41  5376.7 1763.94  5381.9 1764.65  5427.8 1766.04
#Mann=3,-1,0
  4547.5    0.05       0  4980.3    0.05       0  4986.7    0.05       0
Bank Sta=4980.3,4986.7
Exp/Cntr=0.3,0.1

Type RM Length L Ch R = 1,1064,310,310,310
BEGIN DESCRIPTION:
Mapping XS d421787f
END DESCRIPTION:
XS GIS Cut Line= 3
      1641641.82      6894710.01      1641326.50      6895166.10
      1641090.04      6895411.00
#Sta/Elev= 30
  4450.6 1756.89  4454.0 1756.27  4468.9 1756.39  4525.7 1753.46  4713.6 1750.43
  4755.4 1748.52  4776.4 1745.67  4821.0 1747.62  4862.9 1747.34  4885.8 1749.25
  4922.3 1749.26  4970.9 1747.84  4994.0 1745.19  4996.9 1743.91  4997.4 1743.41
  5002.8 1743.41  5003.3 1743.91  5009.8 1744.33  5014.5 1746.86  5021.6 1748.76
  5035.6 1754.80  5063.9 1760.07  5071.1 1760.78  5085.3 1763.45  5092.2 1765.48
  5120.5 1770.43  5170.2 1774.93  5219.6 1780.64  5269.2 1783.29  5345.5 1785.67
#Mann=3,-1,0
  4450.6    0.05       0  4996.9    0.05       0  5003.3    0.05       0
Bank Sta=4996.9,5003.3
Exp/Cntr=0.3,0.1

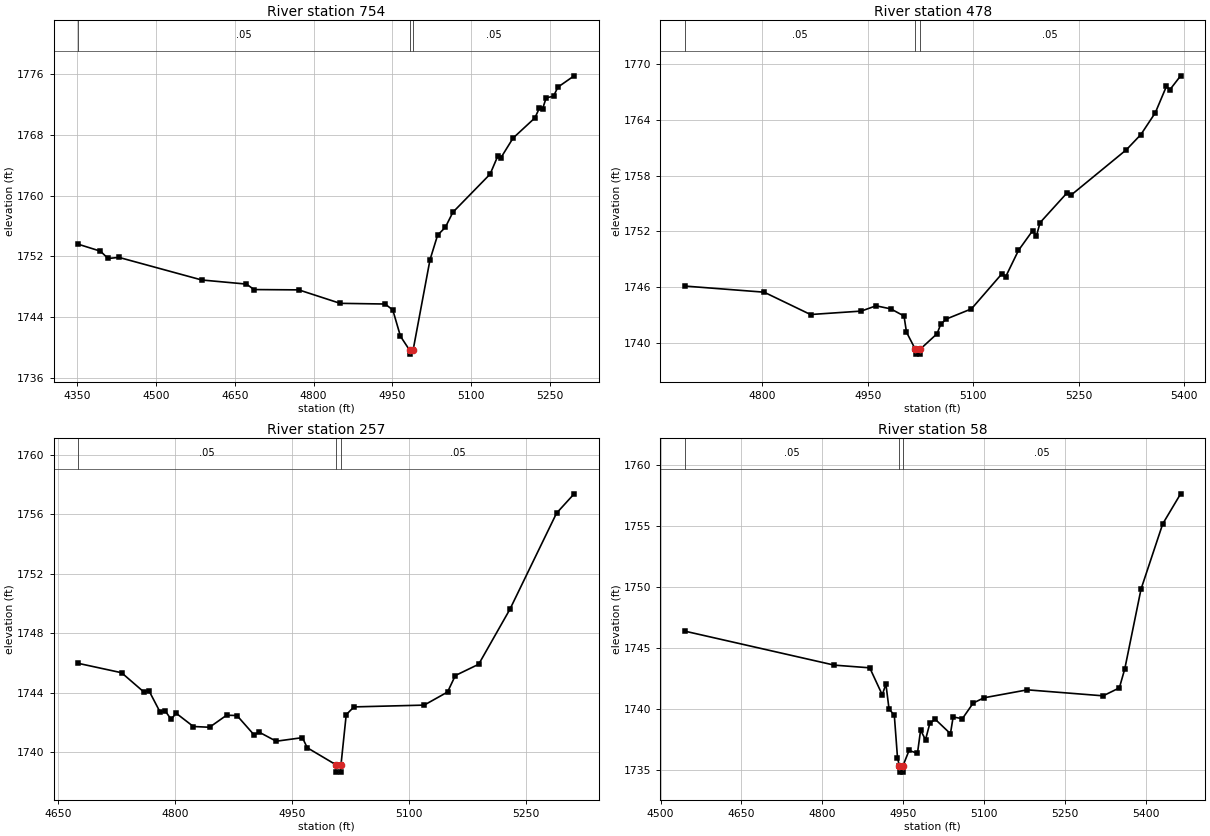
Type RM Length L Ch R = 1,754,276,276,276
BEGIN DESCRIPTION:
Mapping XS a427410b
END DESCRIPTION:
XS GIS Cut Line= 3
      1641633.35      6894507.33      1641208.26      6894836.71
      1640963.35      6895160.43
#Sta/Elev= 30
  4352.4 1753.59  4394.5 1752.68  4408.9 1751.72  4429.8 1751.86  4587.3 1748.89
  4672.4 1748.35  4686.9 1747.63  4772.0 1747.59  4850.7 1745.82  4936.3 1745.73
  4950.9 1744.95  4965.5 1741.49  4983.1 1739.64  4983.6 1739.14  4989.5 1739.64
  5021.7 1751.54  5036.2 1754.79  5050.8 1755.80  5065.3 1757.80  5136.1 1762.81
  5150.7 1765.18  5156.9 1764.99  5179.8 1767.55  5221.4 1770.21  5229.7 1771.46
  5236.0 1771.40  5242.9 1772.85  5256.8 1773.05  5265.1 1774.25  5296.1 1775.74
#Mann=3,-1,0
  4352.4    0.05       0  4983.1    0.05       0  4989.5    0.05       0
Bank Sta=4983.1,4989.5
Exp/Cntr=0.3,0.1

Type RM Length L Ch R = 1,478,221,221,221
BEGIN DESCRIPTION:
Mapping XS 690d6835
END DESCRIPTION:
XS GIS Cut Line= 3
      1641172.56      6894439.21      1641001.28      6894696.13
      1640915.68      6895083.20
#Sta/Elev= 30
  4689.9 1746.09  4802.7 1745.43  4868.7 1743.02  4940.8 1743.39  4961.9 1743.96
  4982.9 1743.63  5001.7 1742.86  5005.2 1741.12  5017.9 1739.25  5018.4 1738.75
  5023.8 1738.75  5024.3 1739.25  5048.8 1740.96  5053.9 1741.98  5062.0 1742.54
  5097.6 1743.63  5141.2 1747.44  5146.3 1747.10  5164.5 1749.94  5184.8 1752.08
  5190.0 1751.49  5195.2 1752.93  5233.6 1756.14  5238.7 1755.86  5318.1 1760.80
  5338.6 1762.43  5359.1 1764.78  5374.8 1767.61  5379.9 1767.27  5395.1 1768.76
#Mann=3,-1,0
  4689.9    0.05       0  5017.9    0.03       0  5024.3    0.05       0
Bank Sta=5017.9,5024.3
Exp/Cntr=0.3,0.1

Type RM Length L Ch R = 1,257,199,199,199
BEGIN DESCRIPTION:
Mapping XS a2319e20
END DESCRIPTION:
XS GIS Cut Line= 3
      1640998.55      6894433.67      1640810.83      6894651.67
      1640801.13      6895000.55
#Sta/Elev= 30
  4675.5 1745.98  4731.0 1745.35  4759.5 1744.06  4766.1 1744.15  4780.4 1742.71
  4787.0 1742.78  4794.6 1742.22  4801.2 1742.62  4823.2 1741.73  4844.0 1741.68
  4865.9 1742.49  4879.2 1742.47  4901.1 1741.17  4907.7 1741.35  4929.6 1740.74
  4963.2 1740.98  4969.5 1740.30  5006.2 1739.16  5006.7 1738.66  5012.3 1738.66
  5012.8 1739.16  5019.5 1742.53  5029.5 1743.05  5119.6 1743.17  5149.6 1744.05
  5159.6 1745.16  5189.6 1745.92  5229.6 1749.61  5289.6 1756.09  5312.2 1757.39
#Mann=3,-1,0
  4675.5    0.05       0  5006.2    0.03       0  5012.8    0.05       0
Bank Sta=5006.2,5012.8
Exp/Cntr=0.3,0.1

Type RM Length L Ch R = 1,58,0,0,0
BEGIN DESCRIPTION:
Deadman 42 1.0
END DESCRIPTION:
XS GIS Cut Line= 3
      1641030.04      6894362.98      1640646.10      6894589.90
      1640683.65      6895061.12
#Sta/Elev= 30
  4545.0 1746.38  4822.0 1743.60  4887.7 1743.38  4910.9 1741.17  4917.6 1742.06
  4923.4 1740.02  4933.2 1739.50  4939.1 1736.03  4942.5 1735.35  4943.0 1734.85
  4948.6 1734.85  4949.1 1735.35  4960.5 1736.62  4976.1 1736.39  4981.9 1738.28
  4991.0 1737.50  4999.1 1738.85  5009.1 1739.17  5037.2 1737.99  5042.2 1739.36
  5059.3 1739.22  5079.4 1740.50  5099.4 1740.93  5179.7 1741.58  5320.1 1741.09
  5350.2 1741.74  5360.3 1743.31  5390.3 1749.81  5430.5 1755.15  5463.7 1757.61
#Mann=3,-1,0
  4545.0    0.05       0  4942.5    0.03       0  4949.1    0.05       0
Bank Sta=4942.5,4949.1
Exp/Cntr=0.3,0.1

Chan Stop Cuts=-1