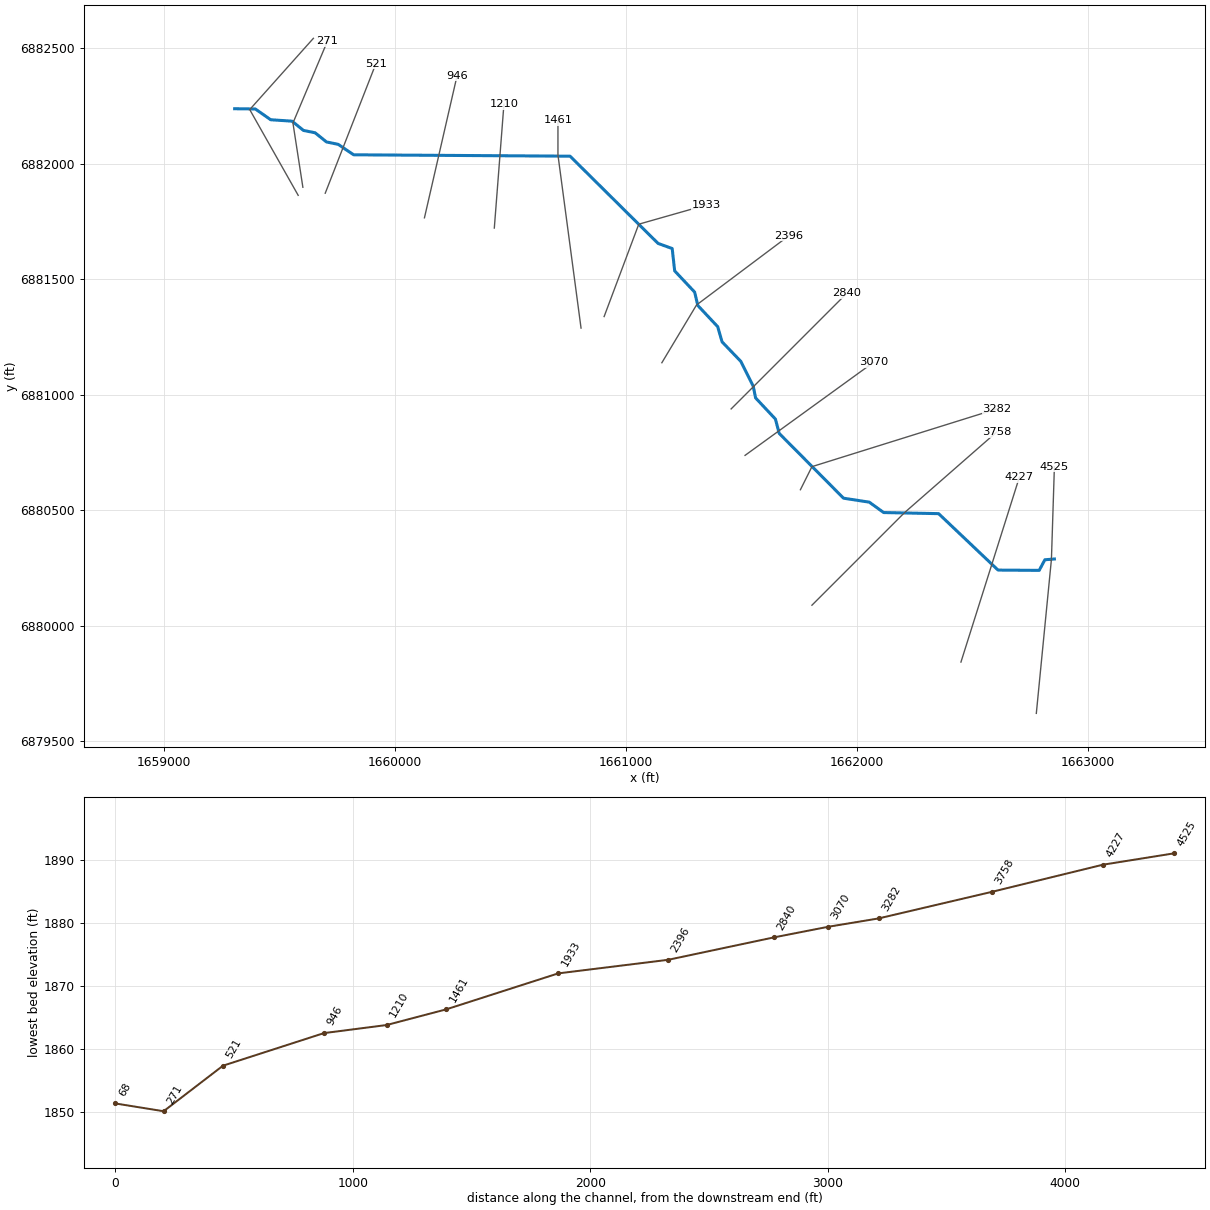
--- Deadman 43.prj (project) ---

Proj Title=Deadman 43 Base Level Engineering
Current Plan=p01
Default Exp/Contr=0.3,0.1
English Units
Geom File=g01
Flow File=f01
Plan File=p01
BEGIN DESCRIPTION:
Deadman 43
END DESCRIPTION:

--- Deadman 43.p01 (plan) ---

Plan Title=Multiple Run
Short Identifier=Multiple
Geom File=g01
Flow File=f01
Subcritical Flow
K Sum by GR= 0
Std Step Tol= 0.01
Critical Tol= 0.01
Num of Std Step Trials= 20
Max Error Tol= 0.3
Flow Tol Ratio= 0.001
Split Flow NTrial= 30
Split Flow Tol= 0.02
Split Flow Ratio= 0.02
Log Output Level= 0
Friction Slope Method= 1
Unsteady Friction Slope Method= 2
Unsteady Bridges Friction Slope Method= 1
Parabolic Critical Depth
Global Vel Dist=  1 , 1 , 1
Global Log Level= 0
CheckData=True
Encroach Param= -1, 0, 0, 0
BEGIN DESCRIPTION:
Multiple Run
END DESCRIPTION:

--- Deadman 43.f01 (steady flow) ---

Flow Title=Multiple
Number of Profiles=7
Profile Names=10-year,25-year,50-year,1pct_min,100-year,1pct_plu,500-year
River Rch & RM= Deadman 43,Reach-1,4525
     339     481     600     374     745    1487    1163
River Rch & RM= Deadman 43,Reach-1,4227
     451     647     815     510    1018    2032    1612
Boundary for River Rch & Prof#=Deadman 43,Reach-1,1
Up Type=0
Dn Type=3
Dn Slope=0.009
Boundary for River Rch & Prof#=Deadman 43,Reach-1,2
Up Type=0
Dn Type=3
Dn Slope=0.009
Boundary for River Rch & Prof#=Deadman 43,Reach-1,3
Up Type=0
Dn Type=3
Dn Slope=0.009
Boundary for River Rch & Prof#=Deadman 43,Reach-1,4
Up Type=0
Dn Type=3
Dn Slope=0.009
Boundary for River Rch & Prof#=Deadman 43,Reach-1,5
Up Type=0
Dn Type=3
Dn Slope=0.009
Boundary for River Rch & Prof#=Deadman 43,Reach-1,6
Up Type=0
Dn Type=3
Dn Slope=0.009
Boundary for River Rch & Prof#=Deadman 43,Reach-1,7
Up Type=0
Dn Type=3
Dn Slope=0.009

--- Deadman 43.g01 (geometry) ---

Geom Title=Existing Conditions

River Reach=Deadman 43,Reach-1
Reach XY= 30
      1662855.00      6880288.00      1662813.69      6880284.76
      1662789.24      6880238.76      1662610.85      6880240.05
      1662353.54      6880484.46      1662115.50      6880489.22
      1662053.40      6880534.14      1661941.70      6880551.40
      1661663.16      6880831.95      1661646.82      6880894.04
      1661560.85      6880985.71      1661550.81      6881036.27
      1661496.84      6881144.05      1661415.80      6881228.33
      1661396.82      6881294.04      1661310.87      6881385.72
      1661296.82      6881444.04      1661210.56      6881535.64
      1661199.74      6881632.53      1661138.55      6881654.74
      1660757.45      6882032.54      1659820.21      6882038.51
      1659753.26      6882083.81      1659702.80      6882094.08
      1659653.28      6882133.84      1659602.82      6882144.12
      1659553.42      6882184.17      1659460.97      6882190.33
      1659394.58      6882236.98      1659305.00      6882238.00

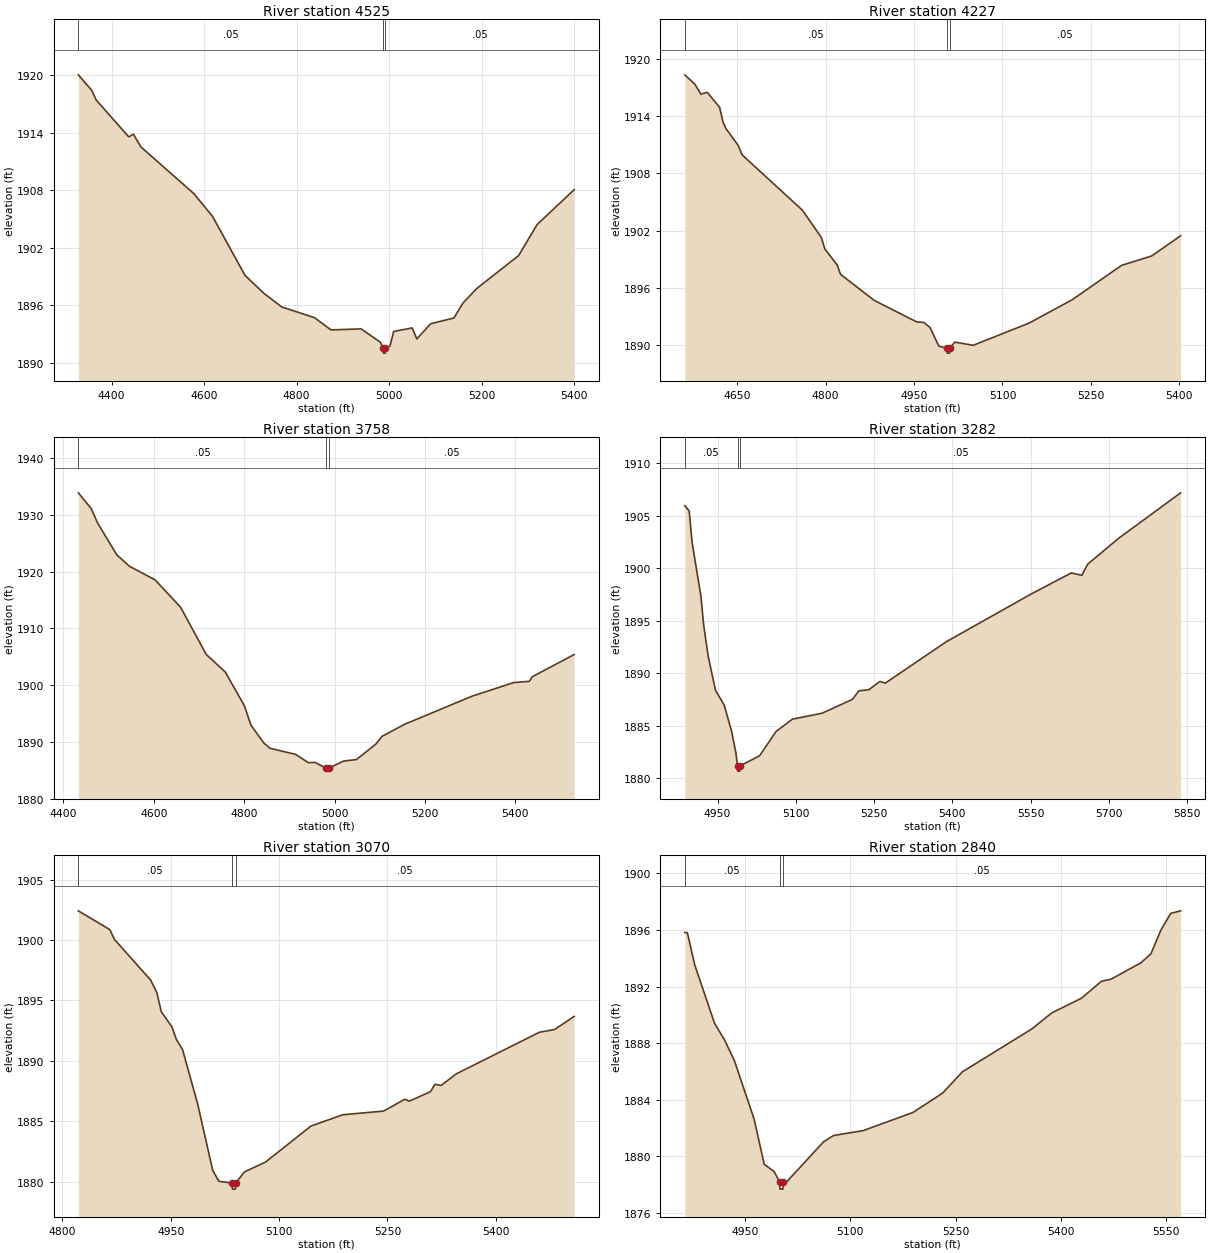
Type RM Length L Ch R = 1,4525,298,298,298
BEGIN DESCRIPTION:
Deadman 43 8.0
END DESCRIPTION:
XS GIS Cut Line= 3
      1662776.69      6879619.47      1662842.16      6880286.98
      1662855.00      6880687.97
#Sta/Elev= 30
  4328.2 1920.02  4356.9 1918.42  4367.0 1917.38  4437.2 1913.55  4447.3 1913.82
  4463.5 1912.50  4577.9 1907.63  4618.1 1905.27  4688.4 1899.11  4728.6 1897.26
  4767.9 1895.81  4839.2 1894.68  4874.4 1893.41  4939.6 1893.52  4980.8 1892.14
  4987.5 1891.49  4987.9 1890.99  4991.9 1890.99  4992.2 1891.49  5001.9 1891.72
  5009.9 1893.25  5050.0 1893.62  5060.0 1892.47  5090.0 1894.06  5140.0 1894.65
  5160.0 1896.23  5190.0 1897.75  5280.1 1901.17  5320.1 1904.41  5400.1 1908.04
#Mann=3,-1,0
  4328.2    0.05       0  4987.5    0.05       0  4992.2    0.05       0
Bank Sta=4987.5,4992.2
Exp/Cntr=0.3,0.1

Type RM Length L Ch R = 1,4227,469,469,469
BEGIN DESCRIPTION:
Mapping XS b4370359
END DESCRIPTION:
XS GIS Cut Line= 2
      1662450.29      6879841.66      1662703.65      6880643.38
#Sta/Elev= 30
  4561.3 1918.30  4578.4 1917.32  4588.6 1916.28  4599.4 1916.47  4620.4 1914.89
  4626.2 1913.34  4631.4 1912.65  4651.8 1910.92  4658.5 1909.93  4760.7 1904.15
  4793.0 1901.28  4798.7 1900.10  4819.6 1898.43  4825.4 1897.44  4882.6 1894.71
  4954.7 1892.46  4966.5 1892.41  4977.0 1891.89  4992.2 1889.93  5006.0 1889.70
  5006.4 1889.20  5010.5 1889.20  5010.8 1889.70  5018.9 1890.35  5050.4 1890.02
  5144.8 1892.33  5218.2 1894.78  5302.1 1898.38  5353.0 1899.36  5402.1 1901.47
#Mann=3,-1,0
  4561.3    0.05       0  5006.0    0.05       0  5010.8    0.05       0
Bank Sta=5006,5010.8
Exp/Cntr=0.3,0.1

Type RM Length L Ch R = 1,3758,476,476,476
BEGIN DESCRIPTION:
Deadman 43 7.0
END DESCRIPTION:
XS GIS Cut Line= 3
      1661805.01      6880088.01      1662205.00      6880488.00
      1662605.02      6880838.02
#Sta/Elev= 30
  4433.0 1933.85  4461.3 1931.11  4475.4 1928.58  4517.8 1922.97  4546.1 1920.93
  4602.7 1918.55  4659.3 1913.73  4715.8 1905.44  4758.2 1902.32  4800.7 1896.35
  4814.8 1893.01  4843.1 1889.86  4857.2 1888.91  4913.8 1887.84  4942.1 1886.37
  4956.2 1886.43  4982.1 1885.39  4982.5 1884.89  4986.6 1884.89  4986.9 1885.39
  5020.0 1886.66  5048.5 1886.93  5091.2 1889.63  5105.0 1891.01  5154.8 1893.12
  5303.8 1898.06  5395.9 1900.46  5431.0 1900.69  5437.6 1901.50  5530.2 1905.40
#Mann=3,-1,0
  4433.0    0.05       0  4982.1    0.05       0  4986.9    0.05       0
Bank Sta=4982.1,4986.9
Exp/Cntr=0.3,0.1

Type RM Length L Ch R = 1,3282,212,212,212
BEGIN DESCRIPTION:
Deadman 43 6.0
END DESCRIPTION:
XS GIS Cut Line= 3
      1661754.98      6880587.97      1661805.00      6880688.00
      1662605.01      6880938.00
#Sta/Elev= 30
  4887.3 1905.94  4895.7 1905.43  4901.3 1902.45  4918.1 1897.35  4923.7 1894.49
  4932.1 1891.62  4946.0 1888.39  4962.8 1886.97  4976.8 1884.51  4985.2 1882.43
  4988.3 1881.19  4988.7 1880.69  4992.8 1880.69  4993.2 1881.19  5030.6 1882.15
  5062.0 1884.45  5093.4 1885.63  5150.5 1886.20  5208.7 1887.52  5220.7 1888.32
  5240.1 1888.44  5261.1 1889.22  5271.5 1889.06  5388.4 1893.00  5550.7 1897.53
  5627.8 1899.54  5648.2 1899.32  5659.2 1900.37  5718.4 1902.83  5837.3 1907.16
#Mann=3,-1,0
  4887.3    0.05       0  4988.3    0.05       0  4993.2    0.05       0
Bank Sta=4988.3,4993.2
Exp/Cntr=0.3,0.1

Type RM Length L Ch R = 1,3070,230,230,230
BEGIN DESCRIPTION:
Mapping XS 1f7fa25f
END DESCRIPTION:
XS GIS Cut Line= 2
      1661515.31      6880736.84      1662071.30      6881139.54
#Sta/Elev= 30
  4822.0 1902.41  4865.7 1900.85  4871.9 1900.05  4922.1 1896.68  4930.7 1895.64
  4936.8 1894.07  4951.5 1892.81  4957.7 1891.77  4966.2 1890.94  4987.1 1886.45
  5008.0 1880.94  5016.5 1880.02  5034.9 1879.87  5035.3 1879.37  5039.5 1879.37
  5039.8 1879.87  5052.1 1880.80  5080.9 1881.60  5144.1 1884.59  5188.2 1885.53
  5244.6 1885.83  5274.0 1886.81  5280.2 1886.65  5309.6 1887.44  5315.8 1888.05
  5324.3 1887.95  5345.2 1888.91  5460.4 1892.36  5481.3 1892.58  5508.5 1893.67
#Mann=3,-1,0
  4822.0    0.05       0  5034.9    0.05       0  5039.8    0.05       0
Bank Sta=5034.9,5039.8
Exp/Cntr=0.3,0.1

Type RM Length L Ch R = 1,2840,444,444,444
BEGIN DESCRIPTION:
Deadman 43 5.0
END DESCRIPTION:
XS GIS Cut Line= 3
      1661454.98      6880937.98      1661555.00      6881038.00
      1661954.98      6881437.98
#Sta/Elev= 30
  4863.9 1895.82  4867.5 1895.82  4878.1 1893.53  4906.4 1889.40  4920.5 1888.24
  4934.6 1886.77  4962.9 1882.61  4977.1 1879.44  4991.2 1878.93  4999.3 1878.18
  4999.7 1877.68  5003.9 1877.68  5004.3 1878.18  5008.9 1878.18  5061.9 1881.03
  5076.1 1881.47  5118.5 1881.82  5189.2 1883.10  5231.6 1884.47  5259.9 1885.98
  5358.9 1889.01  5387.2 1890.14  5429.6 1891.18  5457.9 1892.37  5472.0 1892.53
  5514.5 1893.69  5528.6 1894.32  5542.7 1895.98  5556.9 1897.18  5571.0 1897.36
#Mann=3,-1,0
  4863.9    0.05       0  4999.3    0.05       0  5004.3    0.05       0
Bank Sta=4999.3,5004.3
Exp/Cntr=0.3,0.1

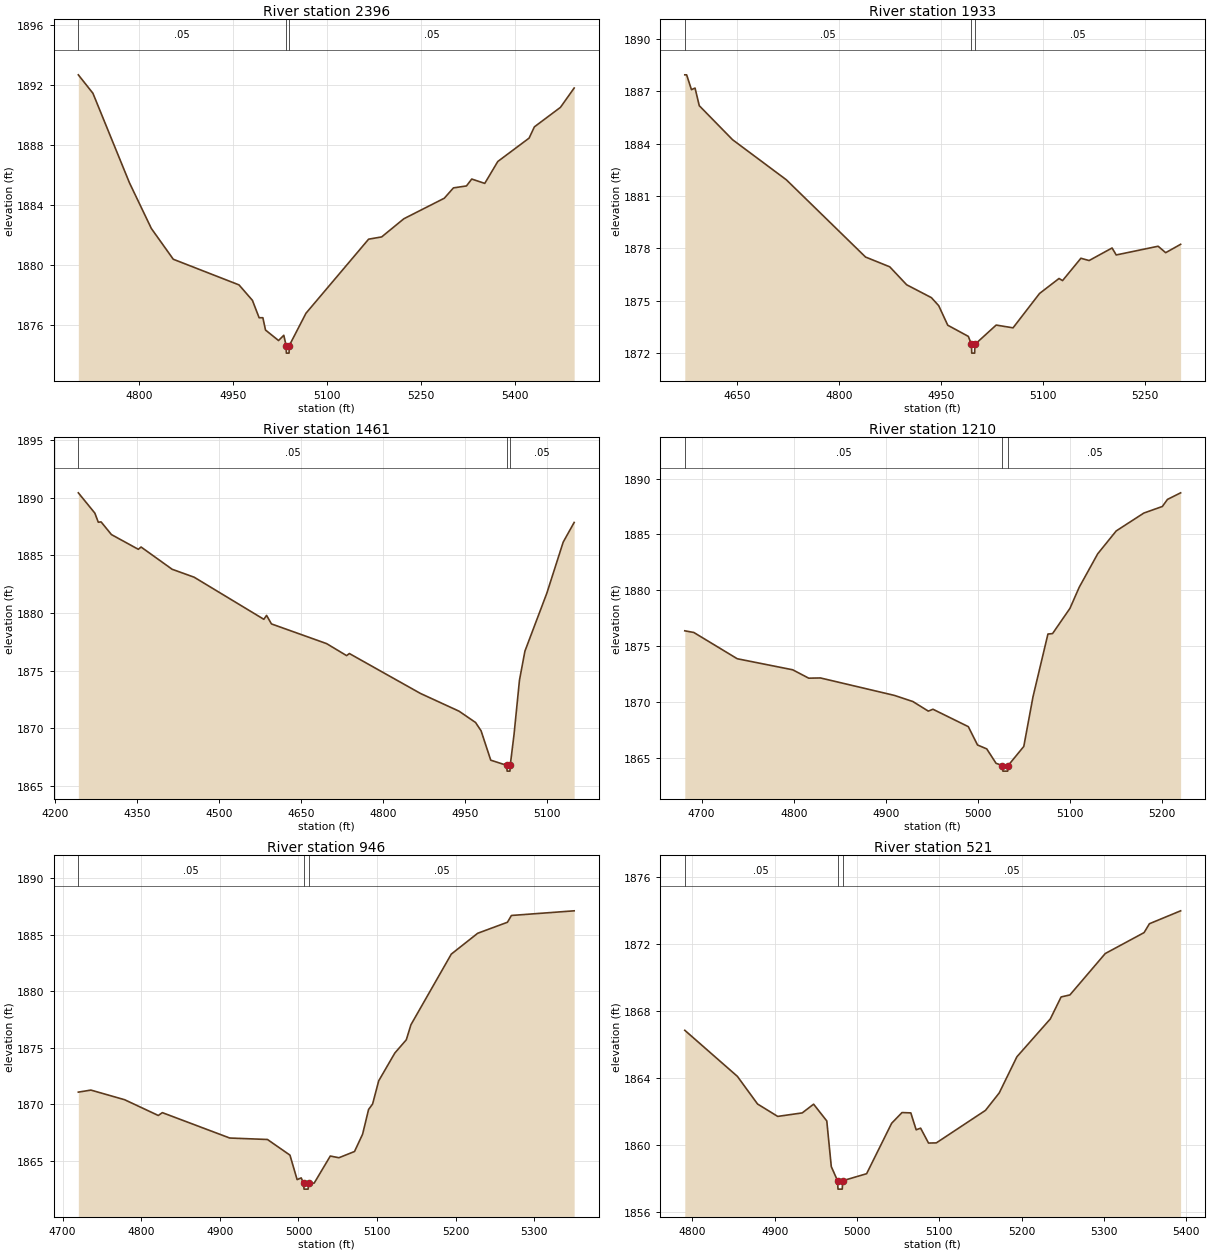
Type RM Length L Ch R = 1,2396,463,463,463
BEGIN DESCRIPTION:
Deadman 43 4.0
END DESCRIPTION:
XS GIS Cut Line= 3
      1661155.02      6881138.04      1661305.00      6881388.00
      1661705.00      6881688.00
#Sta/Elev= 30
  4702.5 1892.70  4725.8 1891.47  4784.1 1885.50  4819.1 1882.45  4854.1 1880.40
  4959.0 1878.69  4980.4 1877.66  4991.1 1876.50  4997.1 1876.50  5001.3 1875.68
  5022.1 1874.98  5030.5 1875.33  5034.2 1874.64  5034.6 1874.14  5038.9 1874.14
  5039.2 1874.64  5065.9 1876.80  5165.9 1881.74  5186.7 1881.89  5222.1 1883.10
  5286.7 1884.47  5301.3 1885.16  5322.1 1885.29  5330.5 1885.75  5351.3 1885.46
  5372.1 1886.92  5422.1 1888.48  5430.5 1889.23  5472.1 1890.53  5494.0 1891.82
#Mann=3,-1,0
  4702.5    0.05       0  5034.2    0.03       0  5039.2    0.05       0
Bank Sta=5034.2,5039.2
Exp/Cntr=0.3,0.1

Type RM Length L Ch R = 1,1933,472,472,472
BEGIN DESCRIPTION:
Deadman 43 3.0
END DESCRIPTION:
XS GIS Cut Line= 3
      1660905.00      6881338.01      1661055.00      6881738.00
      1661346.15      6881820.85
#Sta/Elev= 30
  4572.5 1887.95  4575.2 1887.95  4582.3 1887.10  4587.6 1887.19  4593.8 1886.18
  4642.8 1884.23  4722.0 1881.93  4838.6 1877.50  4874.2 1876.94  4899.1 1875.91
  4935.6 1875.17  4946.3 1874.71  4959.6 1873.59  4989.9 1872.95  4994.5 1872.49
  4994.9 1871.99  4999.2 1871.99  4999.6 1872.49  5030.9 1873.60  5055.7 1873.44
  5094.7 1875.41  5123.4 1876.27  5128.6 1876.15  5155.6 1877.43  5167.7 1877.30
  5201.5 1878.02  5207.6 1877.62  5269.3 1878.12  5280.4 1877.75  5302.4 1878.23
#Mann=3,-1,0
  4572.5    0.05       0  4994.5    0.05       0  4999.6    0.05       0
Bank Sta=4994.5,4999.6
Exp/Cntr=0.3,0.1

Type RM Length L Ch R = 1,1461,251,251,251
BEGIN DESCRIPTION:
Deadman 43 2.0
END DESCRIPTION:
XS GIS Cut Line= 3
      1660805.00      6881288.03      1660705.00      6882038.00
      1660705.00      6882187.99
#Sta/Elev= 30
  4242.9 1890.43  4273.1 1888.67  4279.4 1887.88  4284.5 1887.91  4303.4 1886.81
  4352.6 1885.53  4357.6 1885.73  4414.4 1883.80  4454.7 1883.11  4582.1 1879.46
  4587.1 1879.80  4596.0 1879.06  4696.9 1877.35  4733.4 1876.31  4738.5 1876.49
  4868.4 1873.03  4939.0 1871.49  4969.2 1870.51  4979.3 1869.79  4997.0 1867.24
  5026.4 1866.79  5026.9 1866.29  5032.1 1866.29  5032.6 1866.79  5039.5 1869.44
  5049.5 1874.18  5059.5 1876.70  5099.5 1881.72  5129.5 1886.16  5149.5 1887.86
#Mann=3,-1,0
  4242.9    0.05       0  5026.4    0.05       0  5032.6    0.05       0
Bank Sta=5026.4,5032.6
Exp/Cntr=0.3,0.1

Type RM Length L Ch R = 1,1210,264,264,264
BEGIN DESCRIPTION:
Mapping XS cf4105c3
END DESCRIPTION:
XS GIS Cut Line= 2
      1660429.40      6881721.25      1660471.07      6882257.74
#Sta/Elev= 30
  4681.8 1876.37  4691.6 1876.22  4738.7 1873.87  4798.9 1872.88  4816.3 1872.13
  4829.0 1872.15  4909.2 1870.59  4929.3 1870.04  4946.1 1869.18  4951.1 1869.35
  4989.5 1867.79  4999.5 1866.15  5009.5 1865.80  5019.6 1864.51  5026.5 1864.31
  5027.0 1863.81  5032.2 1863.81  5032.7 1864.31  5049.7 1866.02  5059.7 1870.47
  5075.9 1876.08  5080.9 1876.12  5099.8 1878.38  5109.8 1880.26  5129.9 1883.26
  5150.0 1885.31  5180.0 1886.91  5200.1 1887.50  5205.6 1888.13  5219.9 1888.72
#Mann=3,-1,0
  4681.8    0.05       0  5026.5    0.03       0  5032.7    0.05       0
Bank Sta=5026.5,5032.7
Exp/Cntr=0.3,0.1

Type RM Length L Ch R = 1,946,425,425,425
BEGIN DESCRIPTION:
Mapping XS 934bf15a
END DESCRIPTION:
XS GIS Cut Line= 2
      1660126.83      6881765.60      1660267.96      6882380.31
#Sta/Elev= 30
  4720.0 1871.09  4736.0 1871.27  4778.9 1870.42  4821.7 1869.03  4826.9 1869.28
  4912.6 1867.04  4960.6 1866.91  4989.2 1865.53  4998.3 1863.37  5003.5 1863.52
  5006.6 1863.03  5007.1 1862.53  5012.3 1862.53  5012.8 1863.03  5020.0 1863.06
  5040.5 1865.45  5051.5 1865.30  5071.3 1865.85  5081.6 1867.38  5089.2 1869.56
  5094.3 1870.04  5102.1 1872.09  5122.6 1874.54  5137.2 1875.71  5143.1 1877.04
  5194.4 1883.27  5228.0 1885.11  5265.8 1886.08  5270.9 1886.68  5350.7 1887.09
#Mann=3,-1,0
  4720.0    0.05       0  5006.6    0.03       0  5012.8    0.05       0
Bank Sta=5006.6,5012.8
Exp/Cntr=0.3,0.1

Type RM Length L Ch R = 1,521,250,250,250
BEGIN DESCRIPTION:
Mapping XS d507226c
END DESCRIPTION:
XS GIS Cut Line= 2
      1659697.18      6881872.24      1659916.58      6882433.27
#Sta/Elev= 30
  4790.7 1866.85  4854.6 1864.10  4879.1 1862.45  4903.6 1861.71  4933.4 1861.92
  4947.2 1862.44  4963.2 1861.44  4968.7 1858.71  4976.3 1857.87  4976.8 1857.37
  4982.0 1857.37  4982.5 1857.87  5011.6 1858.29  5042.0 1861.30  5054.6 1861.94
  5065.3 1861.92  5071.8 1860.91  5077.2 1861.01  5086.8 1860.12  5096.3 1860.13
  5156.0 1862.07  5172.7 1863.11  5194.2 1865.27  5234.8 1867.53  5247.9 1868.84
  5258.6 1868.96  5301.5 1871.43  5348.7 1872.68  5355.2 1873.21  5393.1 1873.98
#Mann=3,-1,0
  4790.7    0.05       0  4976.3    0.05       0  4982.5    0.05       0
Bank Sta=4976.3,4982.5
Exp/Cntr=0.3,0.1

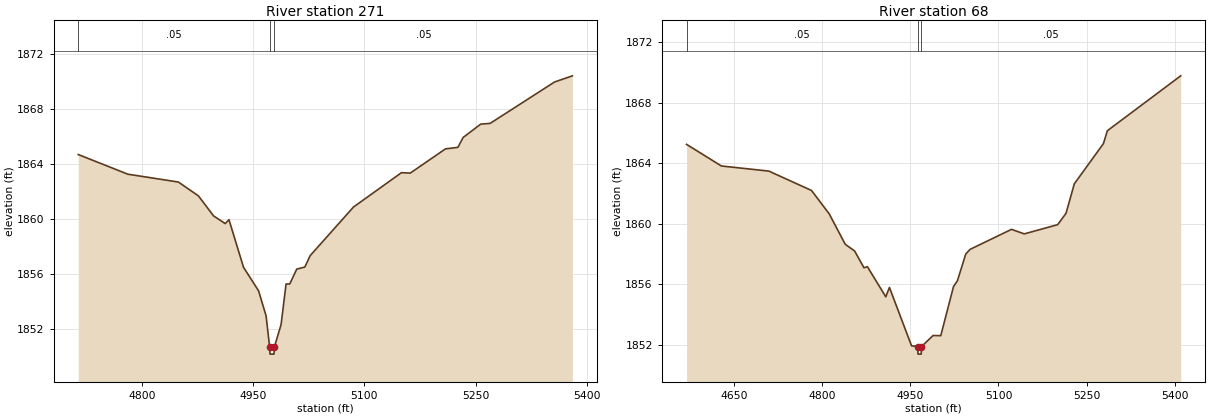
Type RM Length L Ch R = 1,271,203,203,203
BEGIN DESCRIPTION:
Mapping XS 54ee6dcc
END DESCRIPTION:
XS GIS Cut Line= 3
      1659600.33      6881897.88      1659557.32      6882176.15
      1659706.54      6882530.22
#Sta/Elev= 30
  4714.5 1864.67  4781.3 1863.24  4849.4 1862.67  4876.5 1861.66  4896.8 1860.21
  4912.5 1859.65  4917.6 1859.93  4937.2 1856.47  4957.5 1854.76  4967.6 1852.94
  4972.4 1850.66  4972.9 1850.16  4978.2 1850.16  4978.7 1850.66  4987.8 1852.31
  4994.5 1855.26  4999.5 1855.26  5008.9 1856.34  5019.8 1856.49  5027.0 1857.32
  5085.3 1860.85  5150.0 1863.35  5161.9 1863.32  5209.3 1865.08  5226.0 1865.19
  5233.1 1865.91  5256.8 1866.88  5269.4 1866.93  5356.2 1869.94  5380.3 1870.39
#Mann=3,-1,0
  4714.5    0.05       0  4972.4    0.05       0  4978.7    0.05       0
Bank Sta=4972.4,4978.7
Exp/Cntr=0.3,0.1

Type RM Length L Ch R = 1,68,0,0,0
BEGIN DESCRIPTION:
Deadman 43 1.0
END DESCRIPTION:
XS GIS Cut Line= 3
      1659579.99      6881863.01      1659370.15      6882234.32
      1659645.85      6882542.90
#Sta/Elev= 30
  4569.6 1865.26  4628.8 1863.83  4709.6 1863.49  4782.1 1862.21  4812.1 1860.67
  4839.5 1858.65  4855.4 1858.21  4871.3 1857.10  4877.1 1857.17  4908.4 1855.18
  4914.6 1855.80  4952.2 1851.94  4962.7 1851.89  4963.2 1851.39  4968.6 1851.39
  4969.1 1851.89  4988.8 1852.62  5001.9 1852.61  5023.5 1855.85  5030.2 1856.24
  5044.4 1858.01  5051.9 1858.32  5122.2 1859.64  5143.9 1859.34  5200.7 1859.95
  5214.9 1860.70  5229.0 1862.65  5278.5 1865.31  5285.2 1866.16  5409.9 1869.79
#Mann=3,-1,0
  4569.6    0.05       0  4962.7    0.05       0  4969.1    0.05       0
Bank Sta=4962.7,4969.1
Exp/Cntr=0.3,0.1

Chan Stop Cuts=-1